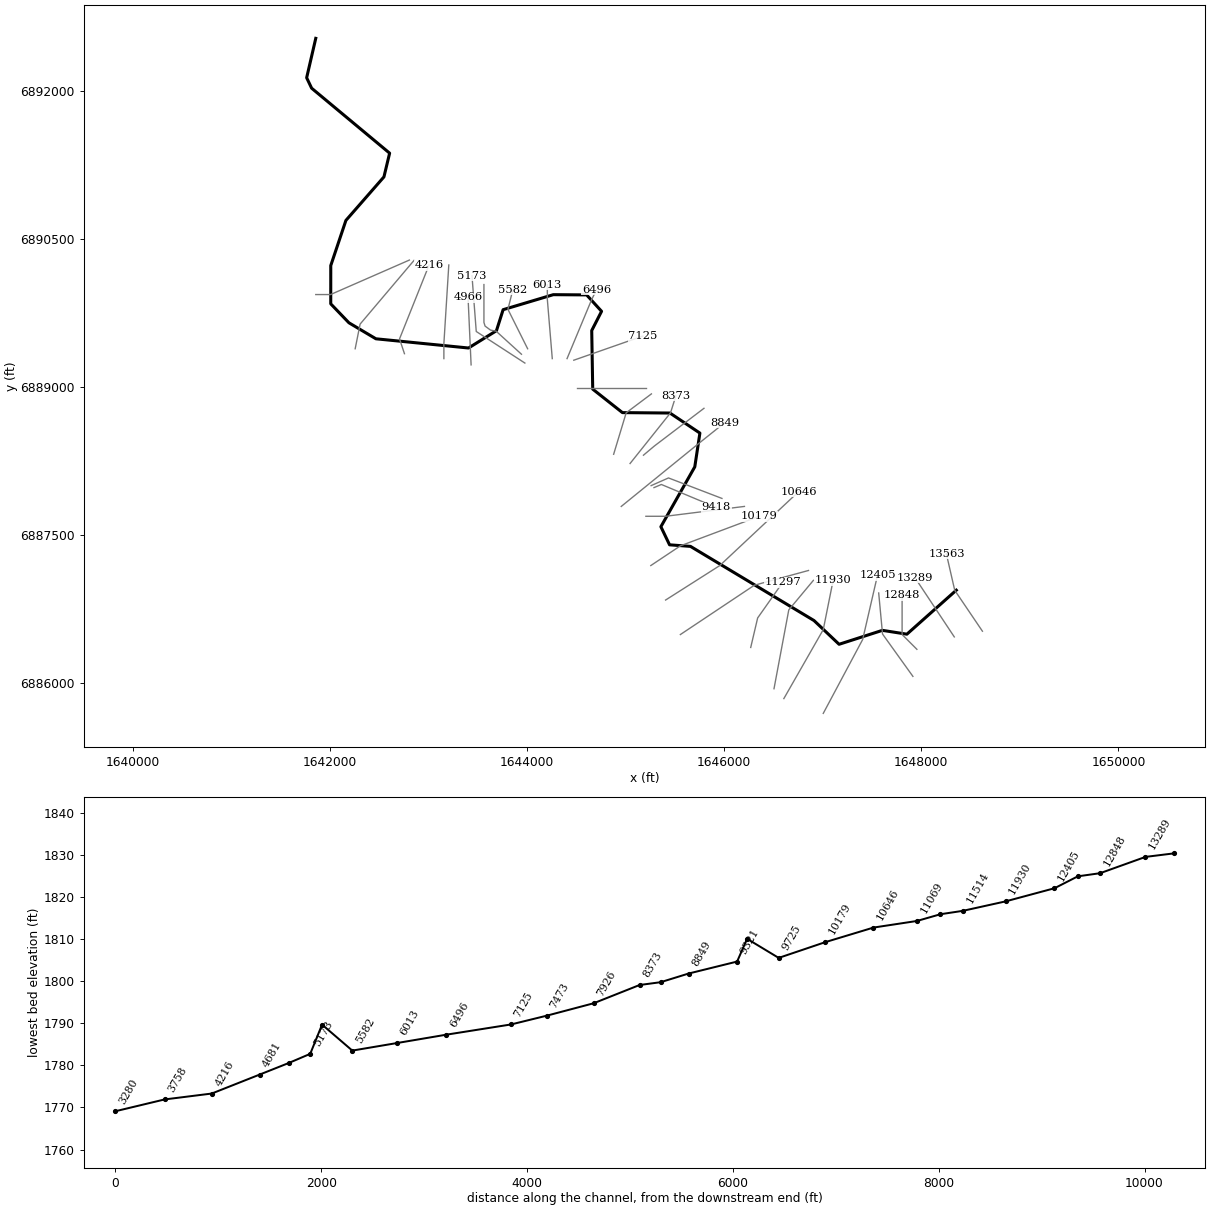
--- Deadman 44.prj (project) ---

Proj Title=Deadman 44 Base Level Engineering
Current Plan=p01
Default Exp/Contr=0.3,0.1
English Units
Geom File=g01
Flow File=f01
Plan File=p01
BEGIN DESCRIPTION:
Deadman 44
END DESCRIPTION:

--- Deadman 44.p01 (plan) ---

Plan Title=Multiple Run
Short Identifier=Multiple
Geom File=g01
Flow File=f01
Subcritical Flow
K Sum by GR= 0
Std Step Tol= 0.01
Critical Tol= 0.01
Num of Std Step Trials= 20
Max Error Tol= 0.3
Flow Tol Ratio= 0.001
Split Flow NTrial= 30
Split Flow Tol= 0.02
Split Flow Ratio= 0.02
Log Output Level= 0
Friction Slope Method= 1
Unsteady Friction Slope Method= 2
Unsteady Bridges Friction Slope Method= 1
Parabolic Critical Depth
Global Vel Dist=  1 , 1 , 1
Global Log Level= 0
CheckData=True
Encroach Param= -1, 0, 0, 0
BEGIN DESCRIPTION:
Multiple Run
END DESCRIPTION:

--- Deadman 44.f01 (steady flow) ---

Flow Title=Multiple
Number of Profiles=7
Profile Names=10-year,25-year,50-year,1pct_min,100-year,1pct_plu,500-year
River Rch & RM= Deadman 44,Reach-1,13563
     210     287     350     213     424     847     631
River Rch & RM= Deadman 44,Reach-1,13289
     361     508     633     392     782    1560    1209
River Rch & RM= Deadman 44,Reach-1,11930
     426     604     756     470     938    1871    1463
River Rch & RM= Deadman 44,Reach-1,5173
     530     761     957     599    1195    2384    1886
Boundary for River Rch & Prof#=Deadman 44,Reach-1,1
Up Type=0
Dn Type=3
Dn Slope=0.005
Boundary for River Rch & Prof#=Deadman 44,Reach-1,2
Up Type=0
Dn Type=3
Dn Slope=0.005
Boundary for River Rch & Prof#=Deadman 44,Reach-1,3
Up Type=0
Dn Type=3
Dn Slope=0.005
Boundary for River Rch & Prof#=Deadman 44,Reach-1,4
Up Type=0
Dn Type=3
Dn Slope=0.005
Boundary for River Rch & Prof#=Deadman 44,Reach-1,5
Up Type=0
Dn Type=3
Dn Slope=0.005
Boundary for River Rch & Prof#=Deadman 44,Reach-1,6
Up Type=0
Dn Type=3
Dn Slope=0.005
Boundary for River Rch & Prof#=Deadman 44,Reach-1,7
Up Type=0
Dn Type=3
Dn Slope=0.005

--- Deadman 44.g01 (geometry) ---

Geom Title=Existing Conditions

River Reach=Deadman 44,Reach-1
Reach XY= 30
      1648355.00      6886938.00      1647853.54      6886491.53
      1647604.99      6886530.47      1647165.44      6886389.04
      1646911.06      6886629.86      1645657.45      6887382.53
      1645445.17      6887398.47      1645357.14      6887582.03
      1645701.17      6888189.58      1645752.94      6888532.15
      1645449.06      6888735.74      1644966.95      6888739.92
      1644665.47      6888978.18      1644655.39      6889572.84
      1644755.22      6889767.95      1644603.54      6889934.46
      1644265.50      6889936.78      1643756.25      6889784.49
      1643688.57      6889571.23      1643405.00      6889395.56
      1642465.43      6889489.05      1642191.70      6889651.40
      1642007.06      6889843.85      1642007.26      6890232.06
      1642160.84      6890690.29      1642546.86      6891131.94
      1642604.52      6891372.80      1641813.12      6892031.95
      1641762.53      6892137.99      1641855.00      6892538.00

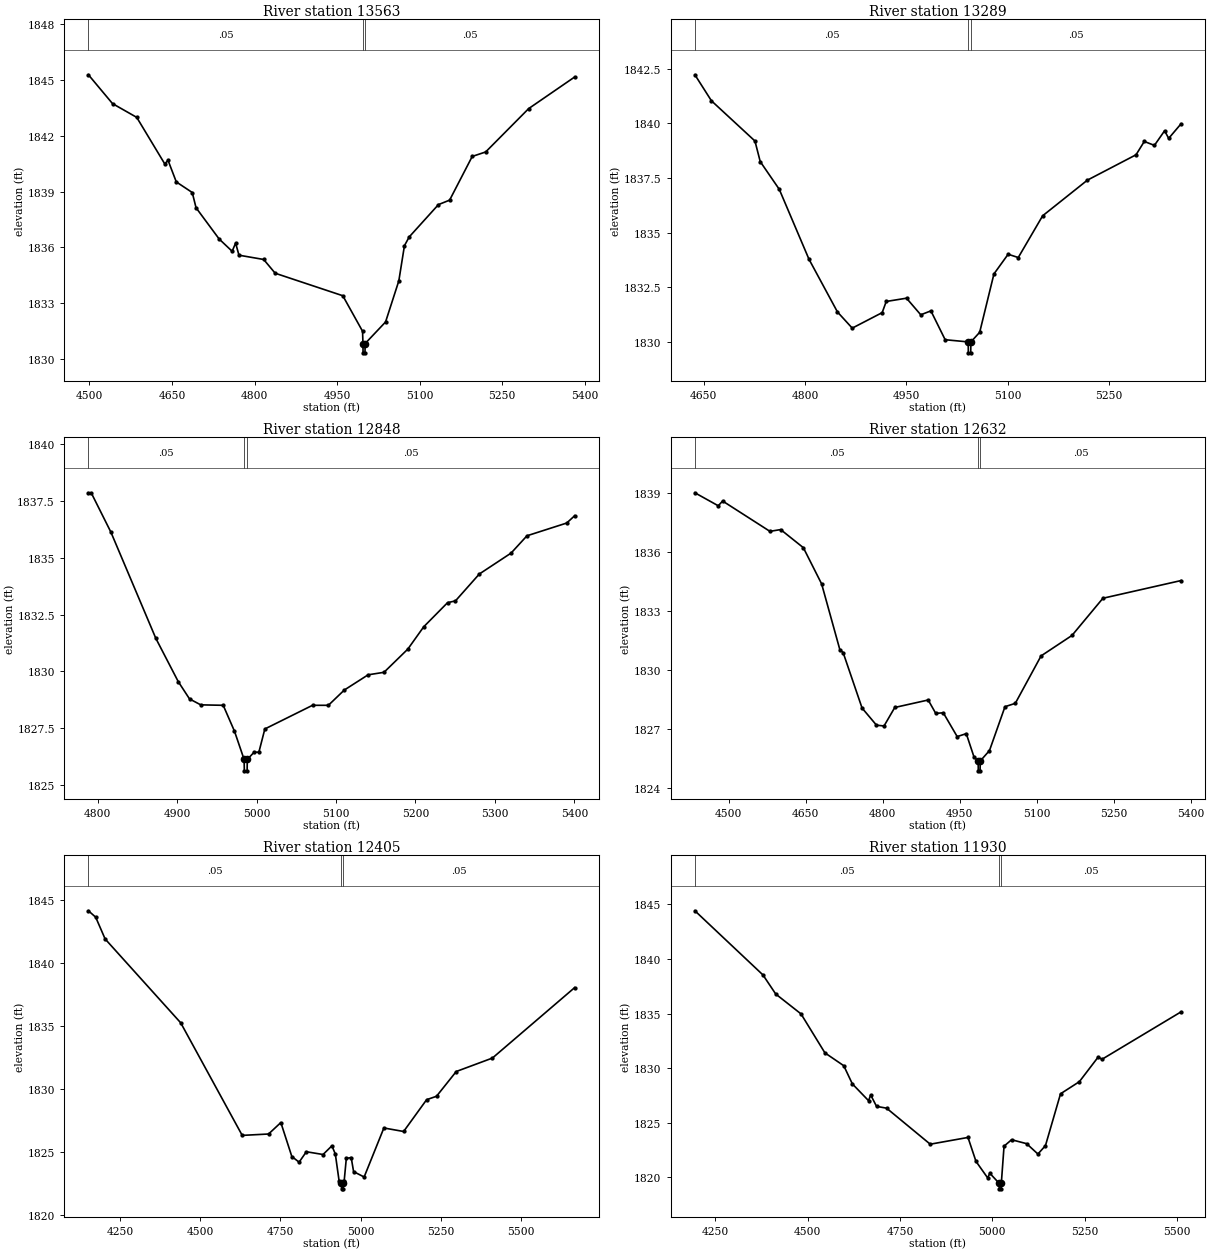
Type RM Length L Ch R = 1,13563,274,274,274
BEGIN DESCRIPTION:
Deadman 44 26.0
END DESCRIPTION:
XS GIS Cut Line= 3
      1648620.12      6886521.70      1648338.85      6886937.38
      1648253.66      6887309.45
#Sta/Elev= 30
  4498.1 1845.28  4541.9 1843.73  4585.9 1842.99  4636.8 1840.49  4642.8 1840.68
  4657.8 1839.52  4686.8 1838.95  4693.7 1838.13  4735.7 1836.45  4759.3 1835.79
  4765.6 1836.23  4771.7 1835.58  4816.6 1835.35  4837.5 1834.61  4960.4 1833.40
  4996.3 1831.49  4997.0 1830.83  4997.2 1830.33  5000.7 1830.33  5001.0 1830.83
  5038.1 1831.99  5062.2 1834.20  5072.4 1836.09  5081.0 1836.56  5134.2 1838.30
  5154.5 1838.54  5195.6 1840.89  5220.0 1841.13  5298.1 1843.46  5381.7 1845.16
#Mann=3,-1,0
  4498.1    0.05       0  4997.0    0.03       0  5001.0    0.05       0
Bank Sta=4997,5001
Exp/Cntr=0.3,0.1

Type RM Length L Ch R = 1,13289,441,441,441
BEGIN DESCRIPTION:
Mapping XS bff4dbf5
END DESCRIPTION:
XS GIS Cut Line= 2
      1648334.47      6886463.93      1647936.64      6887063.56
#Sta/Elev= 30
  4637.0 1842.22  4661.5 1841.03  4725.9 1839.19  4733.7 1838.25  4761.9 1836.98
  4805.9 1833.78  4848.0 1831.37  4869.9 1830.63  4914.2 1831.34  4920.2 1831.85
  4950.2 1832.00  4971.3 1831.24  4986.3 1831.42  5007.4 1830.10  5041.5 1830.00
  5041.7 1829.50  5045.2 1829.50  5045.5 1830.00  5058.5 1830.44  5079.6 1833.11
  5100.6 1834.01  5115.6 1833.86  5151.7 1835.77  5217.9 1837.40  5289.9 1838.56
  5302.1 1839.17  5317.1 1838.99  5332.2 1839.66  5338.2 1839.31  5356.6 1839.98
#Mann=3,-1,0
  4637.0    0.05       0  5041.5    0.03       0  5045.5    0.05       0
Bank Sta=5041.5,5045.5
Exp/Cntr=0.3,0.1

Type RM Length L Ch R = 1,12848,216,216,216
BEGIN DESCRIPTION:
Deadman 44 25.0
END DESCRIPTION:
XS GIS Cut Line= 3
      1647955.01      6886337.99      1647805.00      6886488.00
      1647805.00      6886887.96
#Sta/Elev= 30
  4788.3 1837.85  4791.8 1837.85  4816.6 1836.12  4873.2 1831.45  4901.4 1829.55
  4915.6 1828.79  4929.7 1828.53  4958.0 1828.51  4972.2 1827.37  4984.3 1826.13
  4984.6 1825.63  4988.1 1825.63  4988.3 1826.13  4996.9 1826.45  5002.9 1826.45
  5010.4 1827.47  5070.4 1828.51  5090.4 1828.51  5110.4 1829.18  5140.4 1829.85
  5160.4 1829.96  5190.4 1830.98  5210.4 1831.96  5240.4 1833.02  5250.4 1833.10
  5280.4 1834.28  5320.4 1835.20  5340.4 1835.96  5390.4 1836.52  5400.4 1836.84
#Mann=3,-1,0
  4788.3    0.05       0  4984.3    0.05       0  4988.3    0.05       0
Bank Sta=4984.3,4988.3
Exp/Cntr=0.3,0.1

Type RM Length L Ch R = 1,12632,227,227,227
BEGIN DESCRIPTION:
Mapping XS 1fb5ae4e
END DESCRIPTION:
XS GIS Cut Line= 3
      1647914.59      6886063.33      1647606.45      6886492.99
      1647567.39      6886909.63
#Sta/Elev= 30
  4434.4 1839.02  4479.9 1838.36  4488.5 1838.60  4580.6 1837.06  4601.5 1837.15
  4645.7 1836.23  4681.3 1834.39  4716.9 1831.04  4723.2 1830.90  4760.1 1828.08
  4788.2 1827.21  4802.9 1827.17  4823.8 1828.11  4888.9 1828.49  4903.6 1827.81
  4918.3 1827.84  4945.4 1826.63  4963.1 1826.78  4978.2 1825.59  4986.3 1825.39
  4986.5 1824.89  4990.0 1824.89  4990.3 1825.39  5008.3 1825.92  5038.5 1828.15
  5058.6 1828.32  5108.8 1830.73  5169.0 1831.77  5229.3 1833.66  5381.6 1834.56
#Mann=3,-1,0
  4434.4    0.05       0  4986.3    0.05       0  4990.3    0.05       0
Bank Sta=4986.3,4990.3
Exp/Cntr=0.3,0.1

Type RM Length L Ch R = 1,12405,475,475,475
BEGIN DESCRIPTION:
Deadman 44 24.0
END DESCRIPTION:
XS GIS Cut Line= 3
      1647004.98      6885687.96      1647405.00      6886438.00
      1647554.99      6887087.97
#Sta/Elev= 30
  4150.9 1844.17  4173.6 1843.66  4203.0 1841.93  4438.9 1835.26  4630.8 1826.31
  4713.0 1826.42  4751.3 1827.33  4785.6 1824.63  4808.3 1824.18  4830.9 1825.01
  4883.0 1824.79  4910.6 1825.48  4921.3 1824.83  4932.9 1822.72  4940.4 1822.56
  4940.9 1822.06  4945.6 1822.06  4946.0 1822.56  4948.9 1822.68  4955.6 1824.48
  4970.8 1824.55  4978.3 1823.43  5011.2 1823.00  5072.8 1826.90  5134.4 1826.62
  5206.2 1829.15  5237.0 1829.42  5298.6 1831.39  5411.5 1832.46  5668.0 1838.06
#Mann=3,-1,0
  4150.9    0.05       0  4940.4    0.05       0  4946.0    0.05       0
Bank Sta=4940.4,4946
Exp/Cntr=0.3,0.1

Type RM Length L Ch R = 1,11930,416,416,416
BEGIN DESCRIPTION:
Deadman 44 23.0
END DESCRIPTION:
XS GIS Cut Line= 3
      1646604.98      6885837.97      1647005.00      6886538.00
      1647105.01      6887038.04
#Sta/Elev= 30
  4194.8 1844.42  4379.1 1838.54  4413.7 1836.79  4482.1 1834.97  4546.8 1831.40
  4597.9 1830.22  4621.0 1828.56  4664.9 1827.02  4670.7 1827.54  4686.5 1826.50
  4713.8 1826.33  4831.9 1823.03  4934.1 1823.65  4955.7 1821.46  4987.4 1819.94
  4993.1 1820.37  5018.7 1819.44  5019.1 1818.94  5023.8 1818.94  5024.3 1819.44
  5031.7 1822.85  5052.1 1823.44  5092.8 1823.08  5123.4 1822.13  5143.8 1822.90
  5184.6 1827.65  5235.6 1828.76  5286.6 1831.02  5296.8 1830.81  5511.0 1835.16
#Mann=3,-1,0
  4194.8    0.05       0  5018.7    0.05       0  5024.3    0.05       0
Bank Sta=5018.7,5024.3
Exp/Cntr=0.3,0.1

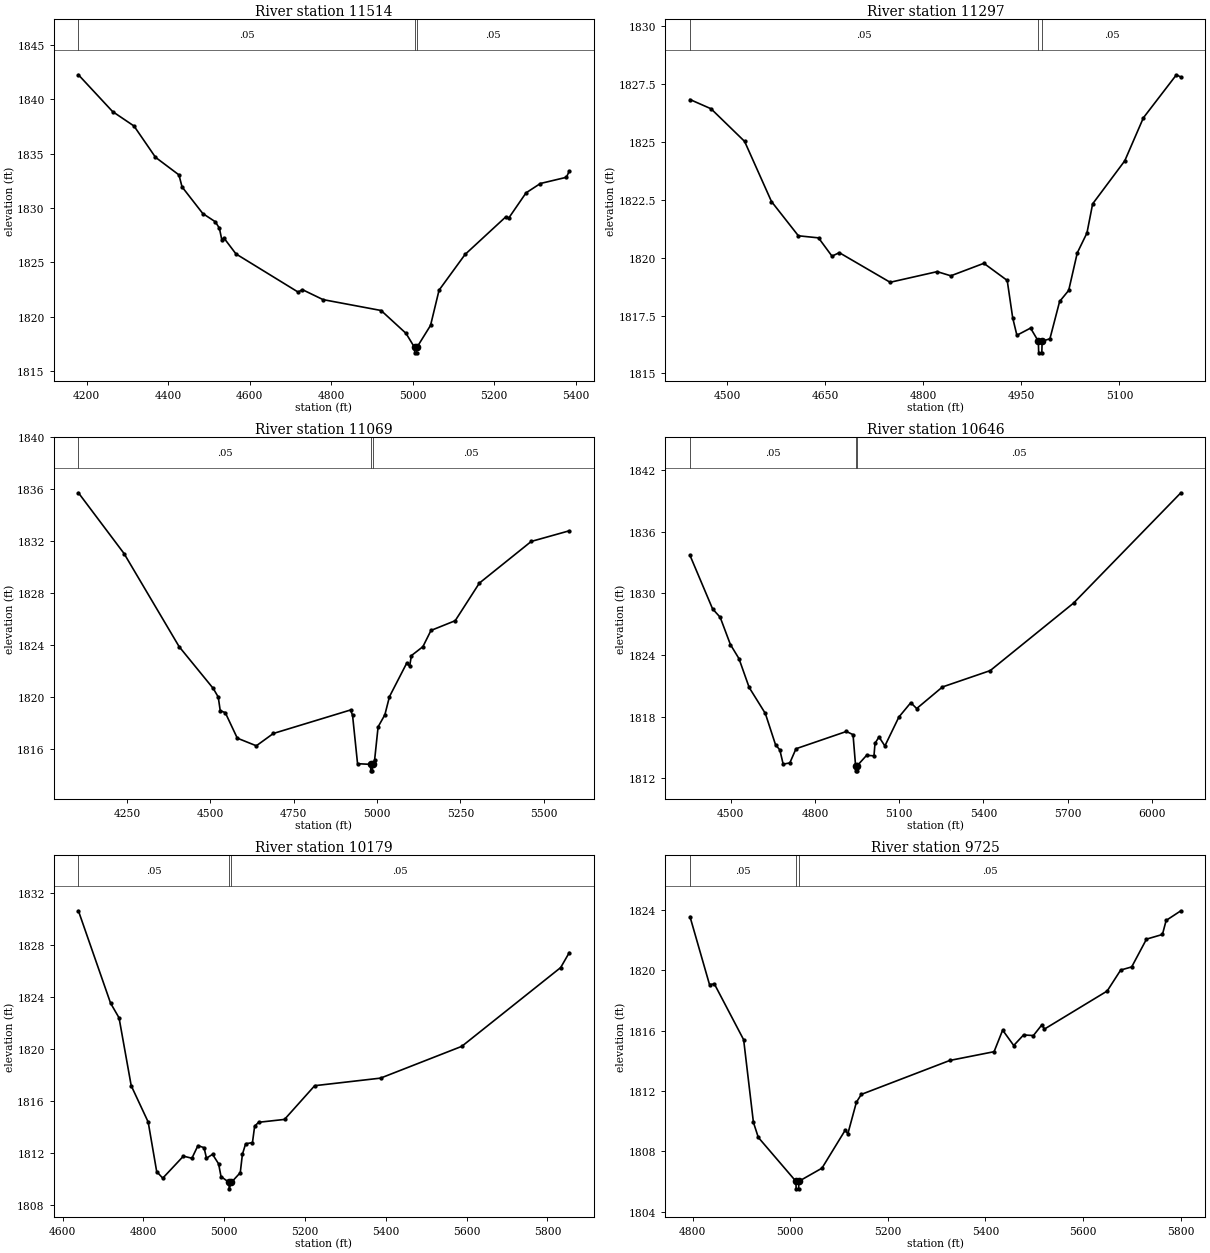
Type RM Length L Ch R = 1,11514,217,217,217
BEGIN DESCRIPTION:
Deadman 44 22.0
END DESCRIPTION:
XS GIS Cut Line= 3
      1646505.00      6885938.01      1646655.00      6886738.00
      1646904.98      6887037.97
#Sta/Elev= 30
  4179.8 1842.24  4263.7 1838.86  4316.3 1837.53  4368.9 1834.66  4426.5 1833.04
  4434.1 1831.94  4485.0 1829.49  4515.5 1828.74  4525.7 1828.15  4531.6 1827.09
  4536.7 1827.25  4566.4 1825.78  4719.0 1822.27  4729.2 1822.50  4780.1 1821.58
  4922.5 1820.58  4983.6 1818.48  5004.5 1817.19  5005.0 1816.69  5009.8 1816.69
  5010.3 1817.19  5043.8 1819.21  5064.7 1822.45  5128.5 1825.73  5228.0 1829.17
  5235.2 1829.05  5278.1 1831.39  5313.3 1832.25  5377.1 1832.82  5384.2 1833.39
#Mann=3,-1,0
  4179.8    0.05       0  5004.5    0.03       0  5010.3    0.05       0
Bank Sta=5004.5,5010.3
Exp/Cntr=0.3,0.1

Type RM Length L Ch R = 1,11297,228,228,228
BEGIN DESCRIPTION:
Mapping XS 9e0688ab
END DESCRIPTION:
XS GIS Cut Line= 3
      1646268.77      6886356.69      1646339.09      6886656.18
      1646594.27      6887018.13
#Sta/Elev= 30
  4443.4 1826.84  4475.6 1826.44  4526.9 1825.03  4568.0 1822.43  4609.1 1820.95
  4639.9 1820.86  4660.5 1820.07  4671.7 1820.22  4749.4 1818.94  4821.3 1819.40
  4842.2 1819.22  4892.7 1819.76  4928.4 1819.02  4936.8 1817.40  4943.2 1816.65
  4964.1 1816.96  4976.0 1816.39  4976.5 1815.89  4981.3 1815.89  4981.8 1816.39
  4993.7 1816.50  5008.5 1818.11  5022.4 1818.59  5035.5 1820.21  5050.3 1821.07
  5059.0 1822.33  5108.1 1824.19  5136.6 1826.05  5187.1 1827.91  5193.9 1827.81
#Mann=3,-1,0
  4443.4    0.05       0  4976.0    0.03       0  4981.8    0.05       0
Bank Sta=4976,4981.8
Exp/Cntr=0.3,0.1

Type RM Length L Ch R = 1,11069,423,423,423
BEGIN DESCRIPTION:
Deadman 44 21.0
END DESCRIPTION:
XS GIS Cut Line= 3
      1645554.96      6886487.97      1646305.00      6886988.00
      1646854.98      6887137.99
#Sta/Elev= 30
  4104.7 1835.72  4241.5 1831.04  4406.7 1823.86  4508.9 1820.64  4523.9 1819.98
  4529.9 1818.92  4544.9 1818.78  4581.0 1816.81  4638.1 1816.22  4689.1 1817.17
  4920.5 1818.98  4926.5 1818.58  4941.5 1814.84  4980.7 1814.79  4981.2 1814.29
  4986.0 1814.29  4986.5 1814.79  4992.6 1815.11  5003.1 1817.68  5023.4 1818.61
  5037.2 1820.01  5089.1 1822.60  5097.7 1822.35  5102.9 1823.17  5137.4 1823.86
  5161.6 1825.11  5234.2 1825.86  5306.7 1828.76  5462.2 1831.97  5576.2 1832.79
#Mann=3,-1,0
  4104.7    0.05       0  4980.7    0.03       0  4986.5    0.05       0
Bank Sta=4980.7,4986.5
Exp/Cntr=0.3,0.1

Type RM Length L Ch R = 1,10646,467,467,467
BEGIN DESCRIPTION:
Deadman 44 20.0
END DESCRIPTION:
XS GIS Cut Line= 3
      1645404.99      6886838.00      1645955.00      6887188.00
      1646754.99      6887937.99
#Sta/Elev= 30
  4354.7 1833.68  4435.1 1828.48  4462.2 1827.66  4498.6 1825.01  4529.1 1823.64
  4565.5 1820.83  4623.1 1818.30  4659.5 1815.25  4674.7 1814.76  4686.6 1813.37
  4710.3 1813.49  4732.3 1814.87  4911.8 1816.55  4935.5 1816.24  4944.5 1813.22
  4944.9 1812.72  4949.8 1812.72  4950.3 1813.22  4983.8 1814.23  5010.1 1814.18
  5013.7 1815.39  5027.9 1816.02  5048.9 1815.14  5098.7 1817.95  5141.2 1819.35
  5162.2 1818.78  5254.0 1820.88  5424.0 1822.47  5721.0 1829.04  6103.2 1839.77
#Mann=3,-1,0
  4354.7    0.05       0  4944.5    0.03       0  4950.3    0.05       0
Bank Sta=4944.5,4950.3
Exp/Cntr=0.3,0.1

Type RM Length L Ch R = 1,10179,454,454,454
BEGIN DESCRIPTION:
Deadman 44 19.0
END DESCRIPTION:
XS GIS Cut Line= 3
      1645255.02      6887188.01      1645555.00      6887388.00
      1646354.97      6887687.99
#Sta/Elev= 30
  4639.1 1830.62  4718.7 1823.53  4739.7 1822.40  4769.8 1817.19  4811.8 1814.40
  4832.9 1810.59  4847.9 1810.09  4899.0 1811.78  4920.0 1811.62  4935.0 1812.59
  4950.1 1812.43  4956.1 1811.62  4971.1 1811.92  4986.1 1811.19  4992.1 1810.21
  5011.8 1809.77  5012.3 1809.27  5017.7 1809.77  5039.7 1810.51  5045.0 1811.92
  5053.0 1812.73  5069.9 1812.82  5075.3 1814.08  5085.1 1814.38  5149.2 1814.60
  5223.9 1817.19  5386.8 1817.77  5587.9 1820.21  5832.7 1826.26  5854.0 1827.41
#Mann=3,-1,0
  4639.1    0.05       0  5011.8    0.05       0  5017.7    0.05       0
Bank Sta=5011.8,5017.7
Exp/Cntr=0.3,0.1

Type RM Length L Ch R = 1,9725,307,307,307
BEGIN DESCRIPTION:
Deadman 44 18.0
END DESCRIPTION:
XS GIS Cut Line= 3
      1645205.00      6887688.00      1645405.00      6887688.00
      1646204.98      6887788.00
#Sta/Elev= 30
  4794.3 1823.56  4834.3 1819.06  4844.3 1819.10  4904.3 1815.40  4924.3 1809.93
  4934.3 1808.93  5011.4 1806.02  5011.9 1805.52  5017.0 1805.52  5017.5 1806.02
  5064.8 1806.89  5112.7 1809.42  5117.8 1809.16  5135.4 1811.26  5145.5 1811.78
  5326.9 1814.03  5417.6 1814.61  5435.2 1816.04  5457.9 1815.02  5478.0 1815.72
  5498.2 1815.68  5515.8 1816.40  5520.9 1816.11  5649.4 1818.63  5677.1 1820.02
  5699.7 1820.23  5730.0 1822.07  5762.7 1822.38  5770.3 1823.31  5800.5 1823.95
#Mann=3,-1,0
  4794.3    0.05       0  5011.4    0.03       0  5017.5    0.05       0
Bank Sta=5011.4,5017.5
Exp/Cntr=0.3,0.1

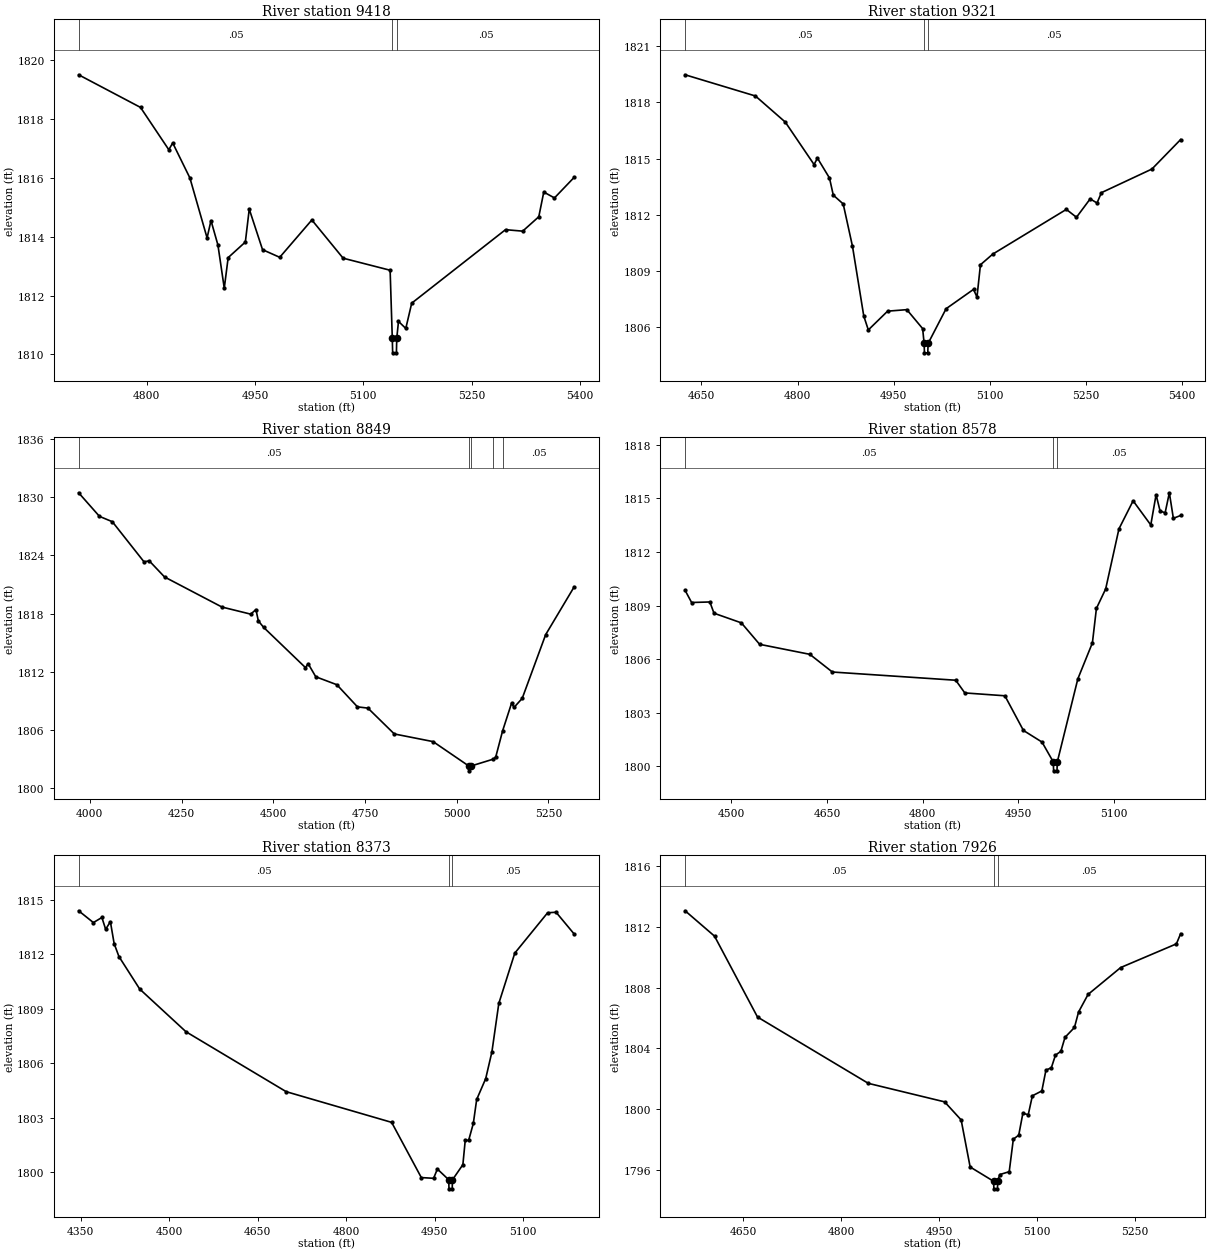
Type RM Length L Ch R = 1,9418,97,97,97
BEGIN DESCRIPTION:
Mapping XS bbb3f983
END DESCRIPTION:
XS GIS Cut Line= 3
      1645287.16      6887978.95      1645362.18      6888010.69
      1645920.18      6887777.29
#Sta/Elev= 30
  4705.7 1819.51  4791.4 1818.40  4830.6 1816.96  4836.0 1817.19  4859.8 1816.00
  4883.6 1813.96  4889.0 1814.55  4898.6 1813.72  4907.4 1812.25  4912.8 1813.29
  4936.6 1813.82  4942.0 1814.94  4960.4 1813.56  4984.2 1813.30  5028.7 1814.57
  5072.0 1813.27  5137.1 1812.86  5140.1 1810.55  5140.6 1810.05  5145.8 1810.05
  5146.3 1810.55  5148.7 1811.12  5158.8 1810.88  5167.0 1811.74  5296.9 1814.24
  5320.7 1814.19  5343.0 1814.68  5349.9 1815.52  5364.7 1815.32  5392.0 1816.02
#Mann=3,-1,0
  4705.7    0.05       0  5140.1    0.03       0  5146.3    0.05       0
Bank Sta=5140.1,5146.3
Exp/Cntr=0.3,0.1

Type RM Length L Ch R = 1,9321,472,472,472
BEGIN DESCRIPTION:
Mapping XS 0f7fad10
END DESCRIPTION:
XS GIS Cut Line= 3
      1645258.27      6887999.14      1645434.33      6888077.06
      1645976.87      6887869.28
#Sta/Elev= 30
  4624.4 1819.46  4734.2 1818.33  4780.8 1816.94  4825.7 1814.68  4831.0 1815.02
  4849.8 1813.96  4855.7 1813.05  4871.2 1812.58  4885.7 1810.32  4903.3 1806.61
  4910.4 1805.87  4940.5 1806.87  4970.5 1806.95  4995.2 1805.94  4997.5 1805.15
  4998.0 1804.65  5003.2 1804.65  5003.7 1805.15  5031.8 1807.00  5074.6 1808.03
  5080.0 1807.62  5085.4 1809.34  5104.7 1809.91  5219.5 1812.29  5235.3 1811.87
  5256.7 1812.85  5267.4 1812.63  5274.2 1813.18  5353.1 1814.44  5397.9 1816.01
#Mann=3,-1,0
  4624.4    0.05       0  4997.5    0.03       0  5003.7    0.05       0
Bank Sta=4997.5,5003.7
Exp/Cntr=0.3,0.1

Type RM Length L Ch R = 1,8849,271,271,271
BEGIN DESCRIPTION:
Deadman 44 17.0
END DESCRIPTION:
XS GIS Cut Line= 3
      1644954.99      6887787.99      1645755.00      6888438.00
      1646005.04      6888638.03
#Sta/Elev= 30
  3969.5 1830.44  4026.3 1828.01  4061.4 1827.46  4147.7 1823.33  4162.0 1823.43
  4203.7 1821.77  4360.3 1818.67  4438.6 1817.94  4452.9 1818.41  4459.4 1817.25
  4473.8 1816.58  4588.0 1812.43  4595.2 1812.84  4616.0 1811.49  4673.5 1810.67
  4729.7 1808.39  4758.2 1808.26  4830.1 1805.60  4935.9 1804.81  5033.2 1802.30
  5033.7 1801.80  5039.5 1802.30  5100.5 1803.01  5106.7 1803.23  5125.4 1805.92
  5150.0 1808.79  5156.4 1808.33  5178.8 1809.26  5242.8 1815.83  5320.5 1820.75
#Mann=5,-1,0
  3969.5    0.05       0  5033.2    0.05       0  5039.5    0.05       0
  5100.5   0.075       0  5125.4    0.05       0
Bank Sta=5033.2,5039.5
Exp/Cntr=0.3,0.1

Type RM Length L Ch R = 1,8578,205,205,205
BEGIN DESCRIPTION:
Mapping XS 1d1cc18e
END DESCRIPTION:
XS GIS Cut Line= 3
      1645180.41      6888307.94      1645290.04      6888400.26
      1645794.31      6888783.51
#Sta/Elev= 30
  4427.5 1809.85  4437.7 1809.17  4466.3 1809.20  4472.8 1808.57  4515.7 1808.03
  4544.3 1806.83  4623.0 1806.27  4658.3 1805.28  4851.7 1804.82  4865.9 1804.11
  4928.7 1803.95  4957.8 1802.01  4986.9 1801.36  5004.6 1800.25  5005.1 1799.75
  5010.4 1799.75  5010.9 1800.25  5043.1 1804.90  5065.9 1806.91  5072.2 1808.84
  5086.7 1809.93  5107.5 1813.29  5129.7 1814.86  5157.4 1813.51  5165.7 1815.20
  5172.0 1814.29  5179.9 1814.19  5186.5 1815.31  5192.8 1813.88  5204.2 1814.04
#Mann=3,-1,0
  4427.5    0.05       0  5004.6    0.03       0  5010.9    0.05       0
Bank Sta=5004.6,5010.9
Exp/Cntr=0.3,0.1

Type RM Length L Ch R = 1,8373,447,447,447
BEGIN DESCRIPTION:
Deadman 44 16.0
END DESCRIPTION:
XS GIS Cut Line= 3
      1645044.41      6888223.42      1645455.00      6888738.00
      1645509.71      6888910.94
#Sta/Elev= 30
  4346.6 1814.39  4371.6 1813.74  4386.0 1814.02  4392.4 1813.37  4400.4 1813.79
  4406.8 1812.58  4414.9 1811.87  4450.1 1810.08  4528.5 1807.73  4698.3 1804.43
  4877.0 1802.74  4927.3 1799.70  4948.1 1799.66  4954.5 1800.17  4973.7 1799.58
  4974.2 1799.08  4979.6 1799.08  4980.1 1799.58  4997.7 1800.41  5001.7 1801.75
  5007.5 1801.75  5015.4 1802.68  5021.1 1804.00  5036.4 1805.15  5046.9 1806.62
  5058.6 1809.29  5085.7 1812.06  5141.3 1814.28  5155.6 1814.31  5186.3 1813.11
#Mann=3,-1,0
  4346.6    0.05       0  4973.7    0.03       0  4980.1    0.05       0
Bank Sta=4973.7,4980.1
Exp/Cntr=0.3,0.1

Type RM Length L Ch R = 1,7926,453,453,453
BEGIN DESCRIPTION:
Deadman 44 15.0
END DESCRIPTION:
XS GIS Cut Line= 3
      1644877.75      6888317.16      1645005.00      6888738.00
      1645261.04      6888930.03
#Sta/Elev= 30
  4560.9 1813.06  4606.0 1811.39  4671.9 1806.06  4841.8 1801.69  4958.8 1800.47
  4984.1 1799.28  4997.9 1796.18  5033.8 1795.24  5034.3 1794.74  5039.7 1794.74
  5040.2 1795.24  5043.3 1795.68  5057.8 1795.87  5064.1 1798.01  5072.4 1798.28
  5078.7 1799.71  5087.0 1799.63  5093.3 1800.87  5107.8 1801.19  5114.1 1802.56
  5122.4 1802.72  5128.7 1803.55  5137.0 1803.80  5143.3 1804.72  5157.8 1805.37
  5164.1 1806.39  5178.7 1807.55  5228.7 1809.32  5314.1 1810.88  5320.6 1811.55
#Mann=3,-1,0
  4560.9    0.05       0  5033.8    0.03       0  5040.2    0.05       0
Bank Sta=5033.8,5040.2
Exp/Cntr=0.3,0.1

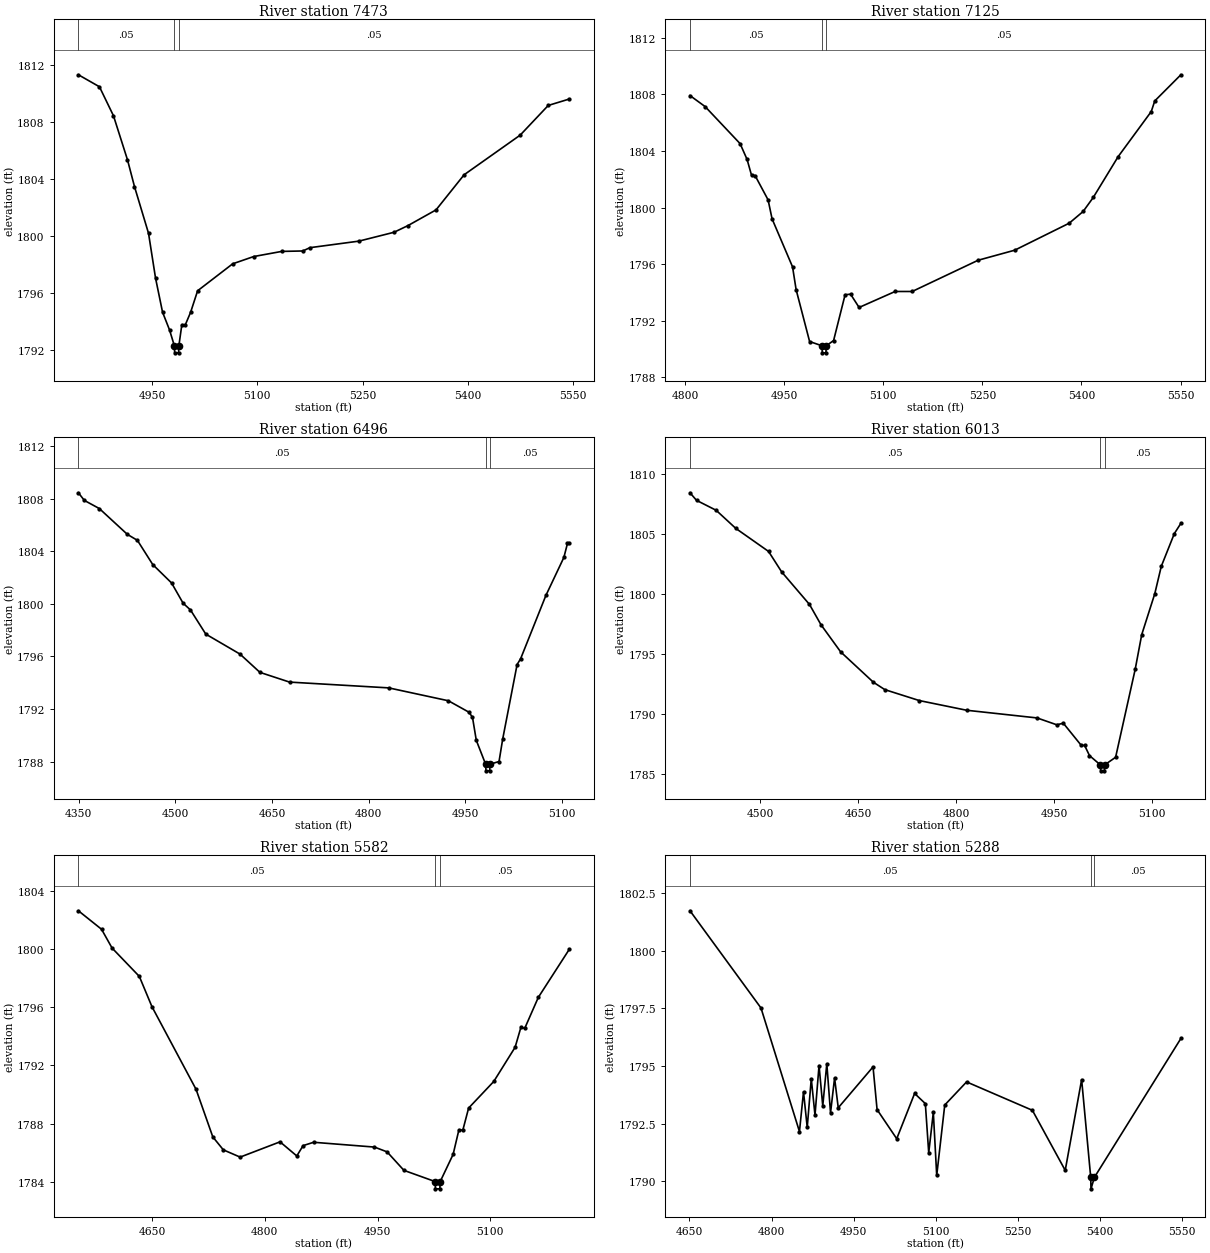
Type RM Length L Ch R = 1,7473,348,348,348
BEGIN DESCRIPTION:
Deadman 44 14.0
END DESCRIPTION:
XS GIS Cut Line= 3
      1644504.99      6888988.00      1644655.00      6888988.00
      1645204.99      6888988.00
#Sta/Elev= 30
  4844.8 1811.30  4874.8 1810.46  4894.8 1808.43  4914.8 1805.34  4924.8 1803.46
  4944.8 1800.19  4954.8 1797.05  4964.8 1794.66  4974.8 1793.41  4981.6 1792.31
  4982.1 1791.81  4987.6 1791.81  4988.1 1792.31  4992.3 1793.78  4997.3 1793.78
  5004.8 1794.65  5014.8 1796.16  5064.8 1798.05  5094.8 1798.56  5134.8 1798.92
  5164.8 1798.95  5174.8 1799.18  5244.8 1799.64  5294.8 1800.26  5314.8 1800.73
  5354.8 1801.83  5394.8 1804.29  5474.8 1807.07  5514.8 1809.15  5544.8 1809.60
#Mann=3,-1,0
  4844.8    0.05       0  4981.6    0.03       0  4988.1    0.05       0
Bank Sta=4981.6,4988.1
Exp/Cntr=0.3,0.1

Type RM Length L Ch R = 1,7125,629,629,629
BEGIN DESCRIPTION:
Mapping XS 2fea60e7
END DESCRIPTION:
XS GIS Cut Line= 2
      1644473.43      6889271.76      1645174.57      6889517.01
#Sta/Elev= 30
  4807.6 1807.92  4830.5 1807.14  4883.4 1804.52  4894.0 1803.40  4900.8 1802.27
  4906.1 1802.26  4925.8 1800.54  4931.8 1799.20  4962.8 1795.80  4968.2 1794.19
  4988.6 1790.52  5007.3 1790.22  5007.8 1789.72  5013.3 1789.72  5013.8 1790.22
  5024.9 1790.59  5042.3 1793.83  5050.6 1793.87  5063.5 1792.93  5118.0 1794.06
  5143.8 1794.06  5243.6 1796.27  5298.9 1796.98  5381.4 1798.89  5402.5 1799.72
  5417.8 1800.71  5455.5 1803.60  5505.6 1806.79  5510.9 1807.54  5550.4 1809.39
#Mann=3,-1,0
  4807.6    0.05       0  5007.3    0.05       0  5013.8    0.05       0
Bank Sta=5007.3,5013.8
Exp/Cntr=0.3,0.1

Type RM Length L Ch R = 1,6496,483,483,483
BEGIN DESCRIPTION:
Deadman 44 13.0
END DESCRIPTION:
XS GIS Cut Line= 3
      1644404.99      6889287.98      1644655.00      6889888.00
      1644704.99      6889987.98
#Sta/Elev= 30
  4349.6 1808.44  4358.8 1807.86  4382.1 1807.24  4425.5 1805.28  4441.2 1804.82
  4465.0 1802.98  4494.2 1801.58  4512.1 1800.04  4523.5 1799.53  4547.3 1797.69
  4600.4 1796.17  4631.3 1794.78  4677.3 1794.04  4831.2 1793.60  4923.8 1792.62
  4955.7 1791.75  4961.2 1791.36  4967.1 1789.61  4981.6 1787.79  4982.1 1787.29
  4987.8 1787.29  4988.3 1787.79  5002.4 1788.00  5008.0 1789.69  5030.4 1795.37
  5036.0 1795.83  5075.1 1800.63  5103.0 1803.52  5108.6 1804.59  5111.4 1804.59
#Mann=3,-1,0
  4349.6    0.05       0  4981.6    0.05       0  4988.3    0.05       0
Bank Sta=4981.6,4988.3
Exp/Cntr=0.3,0.1

Type RM Length L Ch R = 1,6013,431,431,431
BEGIN DESCRIPTION:
Deadman 44 12.0
END DESCRIPTION:
XS GIS Cut Line= 3
      1644255.00      6889288.02      1644205.00      6889888.00
      1644205.00      6890038.04
#Sta/Elev= 30
  4392.4 1808.47  4402.4 1807.84  4432.5 1807.01  4462.6 1805.50  4512.8 1803.58
  4532.9 1801.87  4575.5 1799.16  4593.1 1797.47  4623.2 1795.21  4673.3 1792.68
  4690.9 1792.06  4743.6 1791.15  4816.3 1790.34  4924.2 1789.70  4954.3 1789.13
  4964.4 1789.26  4991.9 1787.41  4997.0 1787.41  5004.5 1786.56  5021.1 1785.79
  5021.6 1785.29  5027.3 1785.29  5027.8 1785.79  5044.5 1786.42  5074.5 1793.75
  5084.5 1796.64  5104.5 1800.05  5114.5 1802.34  5134.5 1805.07  5144.5 1805.92
#Mann=3,-1,0
  4392.4    0.05       0  5021.1    0.03       0  5027.8    0.05       0
Bank Sta=5021.1,5027.8
Exp/Cntr=0.3,0.1

Type RM Length L Ch R = 1,5582,294,294,294
BEGIN DESCRIPTION:
Deadman 44 11.0
END DESCRIPTION:
XS GIS Cut Line= 3
      1644005.02      6889387.96      1643805.00      6889788.00
      1643855.00      6889987.99
#Sta/Elev= 30
  4551.8 1802.62  4582.6 1801.35  4596.6 1800.06  4632.9 1798.11  4649.7 1796.03
  4708.4 1790.35  4730.7 1787.08  4744.7 1786.19  4767.1 1785.69  4820.2 1786.74
  4842.5 1785.77  4850.9 1786.48  4864.9 1786.71  4945.9 1786.38  4962.7 1786.05
  4985.1 1784.78  5026.6 1784.01  5027.1 1783.51  5032.9 1783.51  5033.4 1784.01
  5050.6 1785.88  5058.3 1787.57  5063.5 1787.54  5071.2 1789.06  5104.7 1790.89
  5133.1 1793.24  5140.8 1794.61  5145.9 1794.54  5164.0 1796.67  5205.2 1799.97
#Mann=3,-1,0
  4551.8    0.05       0  5026.6    0.05       0  5033.4    0.05       0
Bank Sta=5026.6,5033.4
Exp/Cntr=0.3,0.1

Type RM Length L Ch R = 1,5288,115,115,115
BEGIN DESCRIPTION:
Mapping XS d1832e18
END DESCRIPTION:
XS GIS Cut Line= 6
      1643942.42      6889332.35      1643685.59      6889566.09
      1643627.88      6889577.63      1643573.05      6889618.03
      1643561.51      6889655.54      1643561.51      6890039.37
#Sta/Elev= 30
  4650.9 1801.72  4780.7 1797.51  4851.0 1792.16  4858.4 1793.88  4865.2 1792.34
  4872.6 1794.45  4879.4 1792.87  4886.8 1795.02  4893.6 1793.27  4901.0 1795.10
  4907.8 1792.97  4915.2 1794.48  4921.9 1793.19  4985.5 1794.96  4992.9 1793.11
  5028.8 1791.85  5061.5 1793.81  5081.1 1793.37  5087.3 1791.24  5095.7 1792.99
  5101.9 1790.26  5116.6 1793.31  5156.5 1794.31  5276.8 1793.08  5336.8 1790.48
  5366.8 1794.41  5383.4 1790.18  5383.9 1789.68  5390.2 1790.18  5548.2 1796.19
#Mann=3,-1,0
  4650.9    0.05       0  5383.4    0.05       0  5390.2    0.05       0
Bank Sta=5383.4,5390.2
Exp/Cntr=0.3,0.1

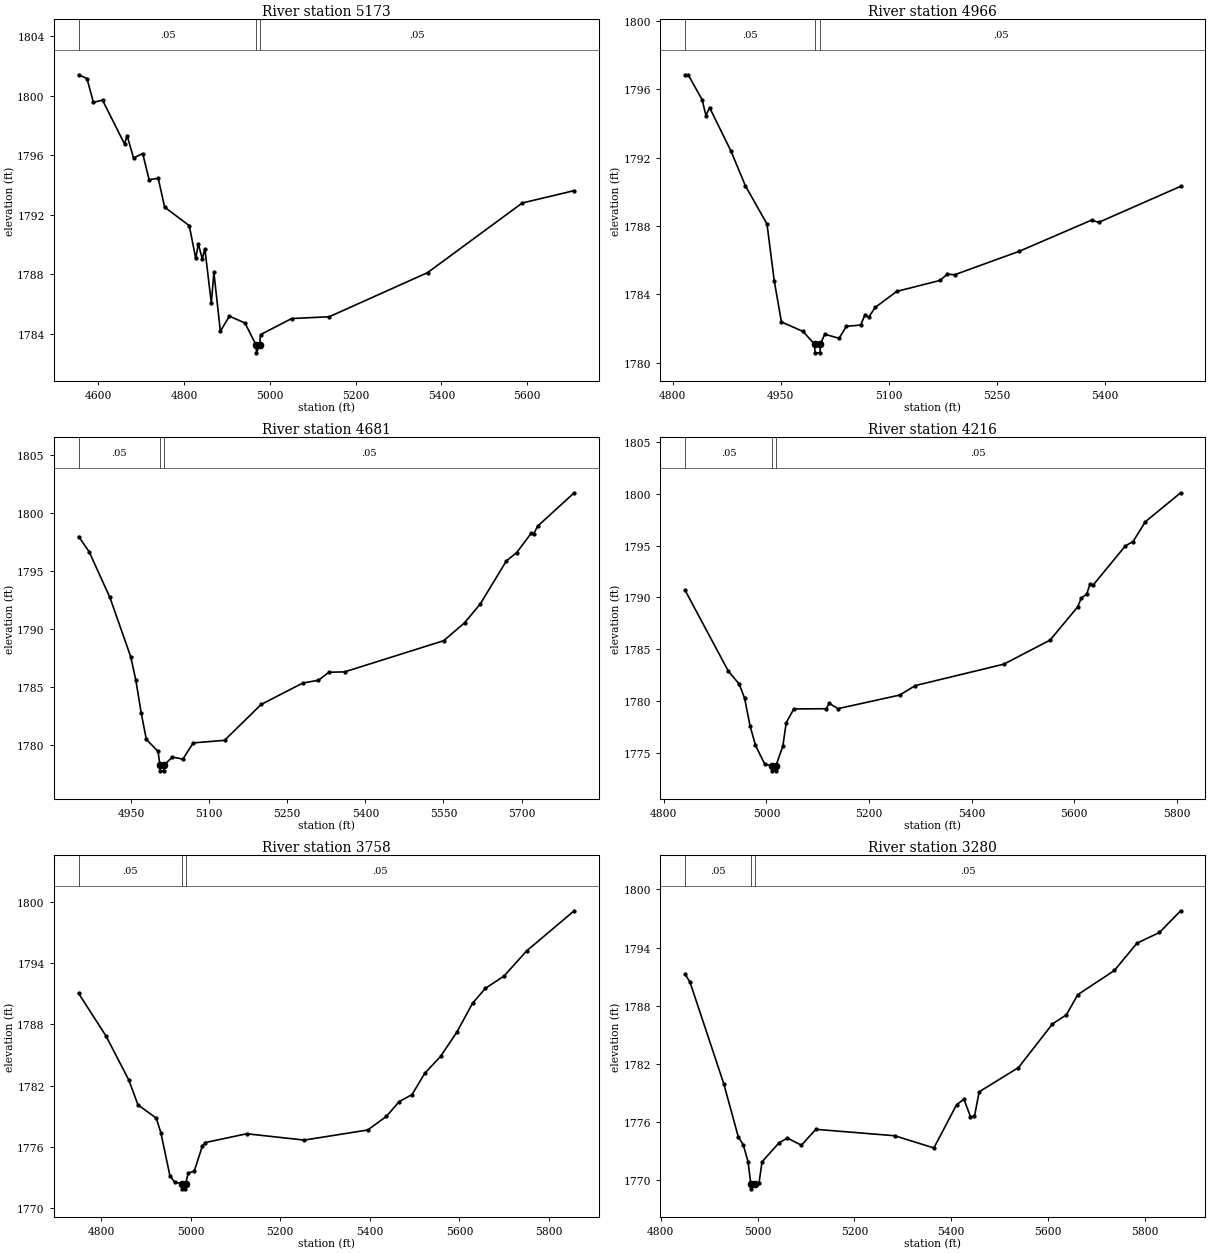
Type RM Length L Ch R = 1,5173,207,207,207
BEGIN DESCRIPTION:
Deadman 44 10.0
END DESCRIPTION:
XS GIS Cut Line= 3
      1643977.01      6889242.91      1643483.59      6889563.20
      1643440.31      6890128.79
#Sta/Elev= 30
  4554.3 1801.39  4573.7 1801.14  4588.8 1799.54  4610.0 1799.69  4661.3 1796.75
  4667.3 1797.31  4682.4 1795.81  4703.6 1796.11  4718.7 1794.35  4739.8 1794.45
  4754.9 1792.51  4812.3 1791.27  4827.4 1789.07  4833.4 1790.04  4842.6 1789.04
  4848.6 1789.72  4863.7 1786.08  4869.7 1788.13  4884.8 1784.19  4905.9 1785.20
  4942.2 1784.74  4968.4 1783.24  4968.9 1782.74  4976.4 1783.24  4978.4 1783.96
  5050.9 1785.04  5138.6 1785.16  5368.0 1788.12  5588.7 1792.79  5709.8 1793.62
#Mann=3,-1,0
  4554.3    0.05       0  4968.4    0.03       0  4976.4    0.05       0
Bank Sta=4968.4,4976.4
Exp/Cntr=0.3,0.1

Type RM Length L Ch R = 1,4966,285,285,285
BEGIN DESCRIPTION:
Mapping XS c3fcd955
END DESCRIPTION:
XS GIS Cut Line= 2
      1643431.32      6889224.41      1643400.26      6889911.61
#Sta/Elev= 30
  4817.4 1796.86  4821.7 1796.86  4841.0 1795.40  4846.4 1794.47  4851.4 1794.94
  4881.1 1792.39  4901.1 1790.36  4931.1 1788.12  4941.1 1784.81  4951.1 1782.39
  4981.2 1781.83  4997.2 1781.08  4997.7 1780.58  5004.7 1780.58  5005.2 1781.08
  5011.2 1781.67  5031.2 1781.43  5041.2 1782.13  5061.2 1782.21  5067.2 1782.82
  5072.2 1782.66  5081.3 1783.24  5111.3 1784.18  5171.4 1784.82  5181.4 1785.19
  5191.4 1785.15  5281.5 1786.53  5381.6 1788.35  5391.6 1788.22  5505.3 1790.33
#Mann=3,-1,0
  4817.4    0.05       0  4997.2    0.03       0  5005.2    0.05       0
Bank Sta=4997.2,5005.2
Exp/Cntr=0.3,0.1

Type RM Length L Ch R = 1,4681,465,465,465
BEGIN DESCRIPTION:
Deadman 44 9.0
END DESCRIPTION:
XS GIS Cut Line= 3
      1643155.00      6889288.01      1643155.00      6889438.00
      1643205.00      6890238.05
#Sta/Elev= 30
  4849.4 1798.01  4869.4 1796.71  4909.4 1792.76  4949.4 1787.65  4959.4 1785.60
  4969.4 1782.83  4979.4 1780.52  5001.9 1779.49  5005.4 1778.31  5005.9 1777.81
  5013.0 1777.81  5013.5 1778.31  5029.5 1779.00  5049.5 1778.82  5069.5 1780.22
  5129.6 1780.44  5199.8 1783.53  5279.9 1785.38  5310.0 1785.62  5330.0 1786.31
  5360.1 1786.34  5550.5 1789.03  5590.5 1790.57  5620.6 1792.19  5670.7 1795.90
  5690.7 1796.63  5718.3 1798.28  5723.3 1798.25  5730.8 1798.90  5801.0 1801.78
#Mann=3,-1,0
  4849.4    0.05       0  5005.4    0.03       0  5013.5    0.05       0
Bank Sta=5005.4,5013.5
Exp/Cntr=0.3,0.1

Type RM Length L Ch R = 1,4216,458,458,458
BEGIN DESCRIPTION:
Deadman 44 8.0
END DESCRIPTION:
XS GIS Cut Line= 3
      1642755.01      6889337.97      1642705.00      6889488.00
      1643004.99      6890237.98
#Sta/Elev= 30
  4841.5 1790.69  4925.9 1782.90  4946.9 1781.67  4957.5 1780.30  4968.0 1777.66
  4978.6 1775.78  4997.0 1773.93  5010.4 1773.81  5010.9 1773.31  5018.1 1773.31
  5018.6 1773.81  5032.0 1775.70  5038.7 1777.96  5053.5 1779.27  5116.8 1779.29
  5122.2 1779.81  5139.7 1779.30  5259.5 1780.60  5290.4 1781.52  5462.8 1783.58
  5553.0 1785.90  5606.8 1789.10  5613.6 1789.93  5624.3 1790.33  5631.1 1791.33
  5636.4 1791.17  5699.7 1794.97  5714.5 1795.38  5738.8 1797.30  5807.4 1800.08
#Mann=3,-1,0
  4841.5    0.05       0  5010.4    0.05       0  5018.6    0.05       0
Bank Sta=5010.4,5018.6
Exp/Cntr=0.3,0.1

Type RM Length L Ch R = 1,3758,478,478,478
BEGIN DESCRIPTION:
Deadman 44 7.0
END DESCRIPTION:
XS GIS Cut Line= 3
      1642255.01      6889388.04      1642305.00      6889638.00
      1642855.01      6890288.02
#Sta/Elev= 30
  4749.9 1791.03  4811.0 1786.87  4862.0 1782.55  4882.4 1780.13  4923.2 1778.83
  4933.4 1777.42  4953.8 1773.18  4964.0 1772.58  4980.2 1772.41  4980.7 1771.91
  4988.2 1771.91  4988.7 1772.41  4994.6 1773.44  5008.1 1773.65  5026.2 1776.11
  5032.8 1776.44  5125.1 1777.30  5253.7 1776.68  5395.4 1777.67  5437.1 1779.00
  5465.7 1780.45  5494.3 1781.13  5522.8 1783.22  5558.0 1784.87  5594.3 1787.24
  5629.4 1790.07  5658.0 1791.53  5699.7 1792.73  5750.3 1795.20  5856.3 1799.12
#Mann=3,-1,0
  4749.9    0.05       0  4980.2    0.05       0  4988.7    0.05       0
Bank Sta=4980.2,4988.7
Exp/Cntr=0.3,0.1

Type RM Length L Ch R = 1,3280,466,466,466
BEGIN DESCRIPTION:
Deadman 44 6.0
END DESCRIPTION:
XS GIS Cut Line= 3
      1641855.02      6889938.00      1642005.00      6889938.00
      1642805.00      6890288.00
#Sta/Elev= 30
  4850.5 1791.25  4860.5 1790.45  4930.5 1779.93  4960.5 1774.44  4970.5 1773.68
  4980.5 1771.90  4986.2 1769.61  4986.7 1769.11  4994.8 1769.61  5003.2 1769.74
  5009.4 1771.90  5044.1 1773.84  5061.7 1774.35  5090.5 1773.61  5120.5 1775.25
  5283.1 1774.59  5364.2 1773.33  5411.0 1777.78  5426.2 1778.36  5439.8 1776.55
  5448.0 1776.59  5457.7 1779.12  5538.8 1781.62  5609.0 1786.12  5637.9 1787.07
  5661.2 1789.14  5736.9 1791.64  5783.6 1794.46  5830.0 1795.56  5873.7 1797.80
#Mann=3,-1,0
  4850.5    0.05       0  4986.2    0.05       0  4994.8    0.05       0
Bank Sta=4986.2,4994.8
Exp/Cntr=0.3,0.1