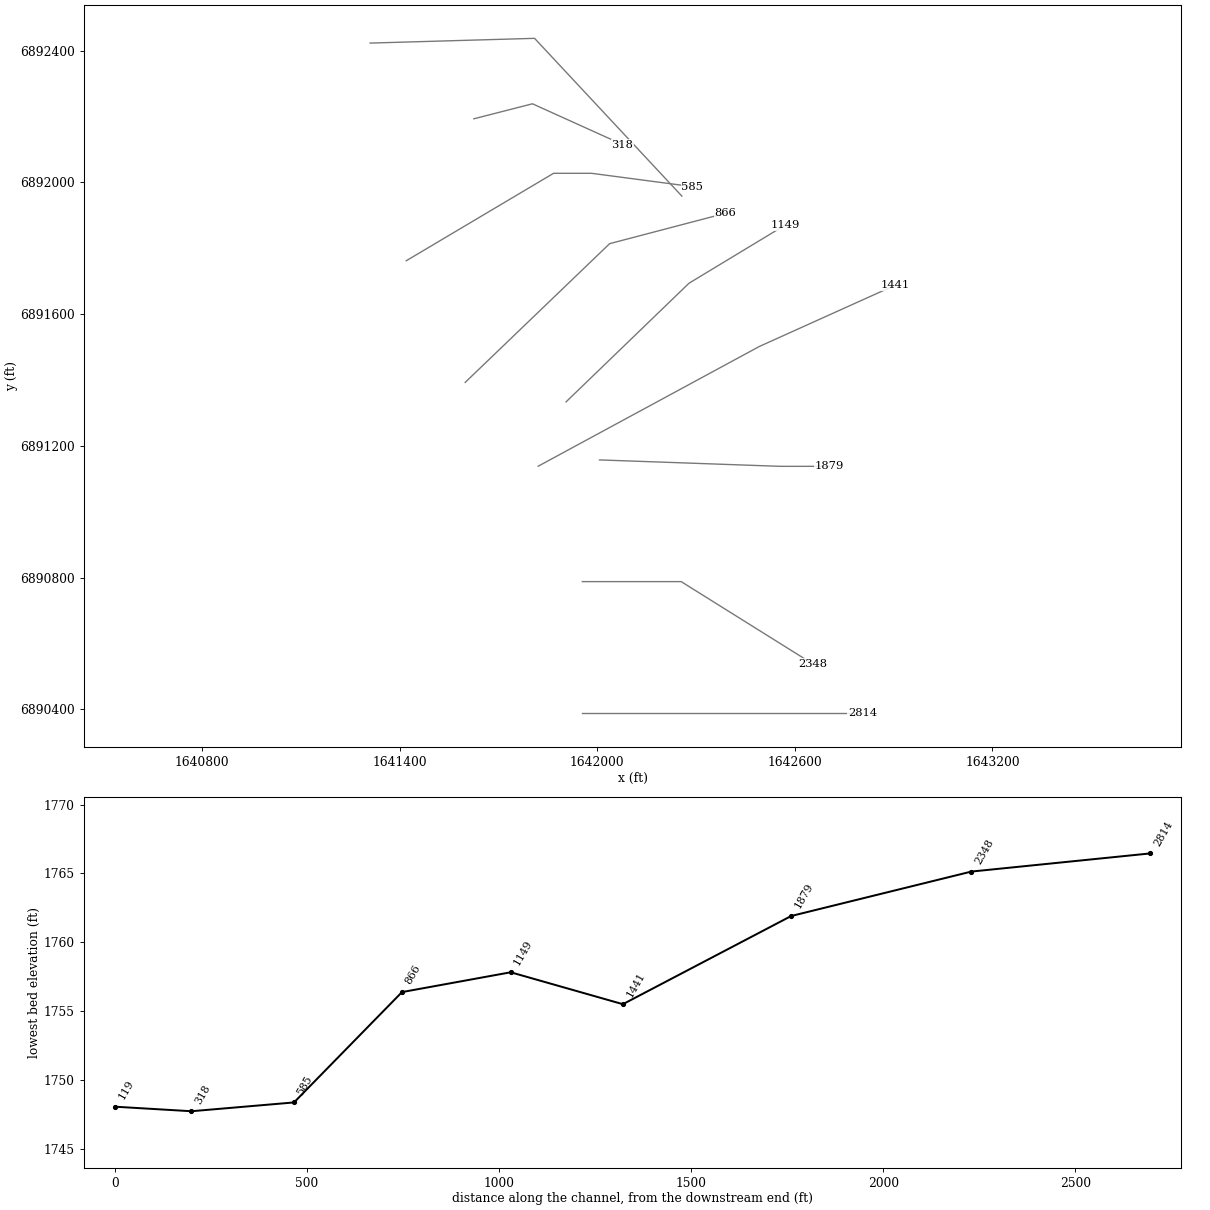
HEC-RAS study Deadman 44.prj: Deadman 44 Base Level Engineering

--- Deadman 44.g01 (geometry) --- (continued)

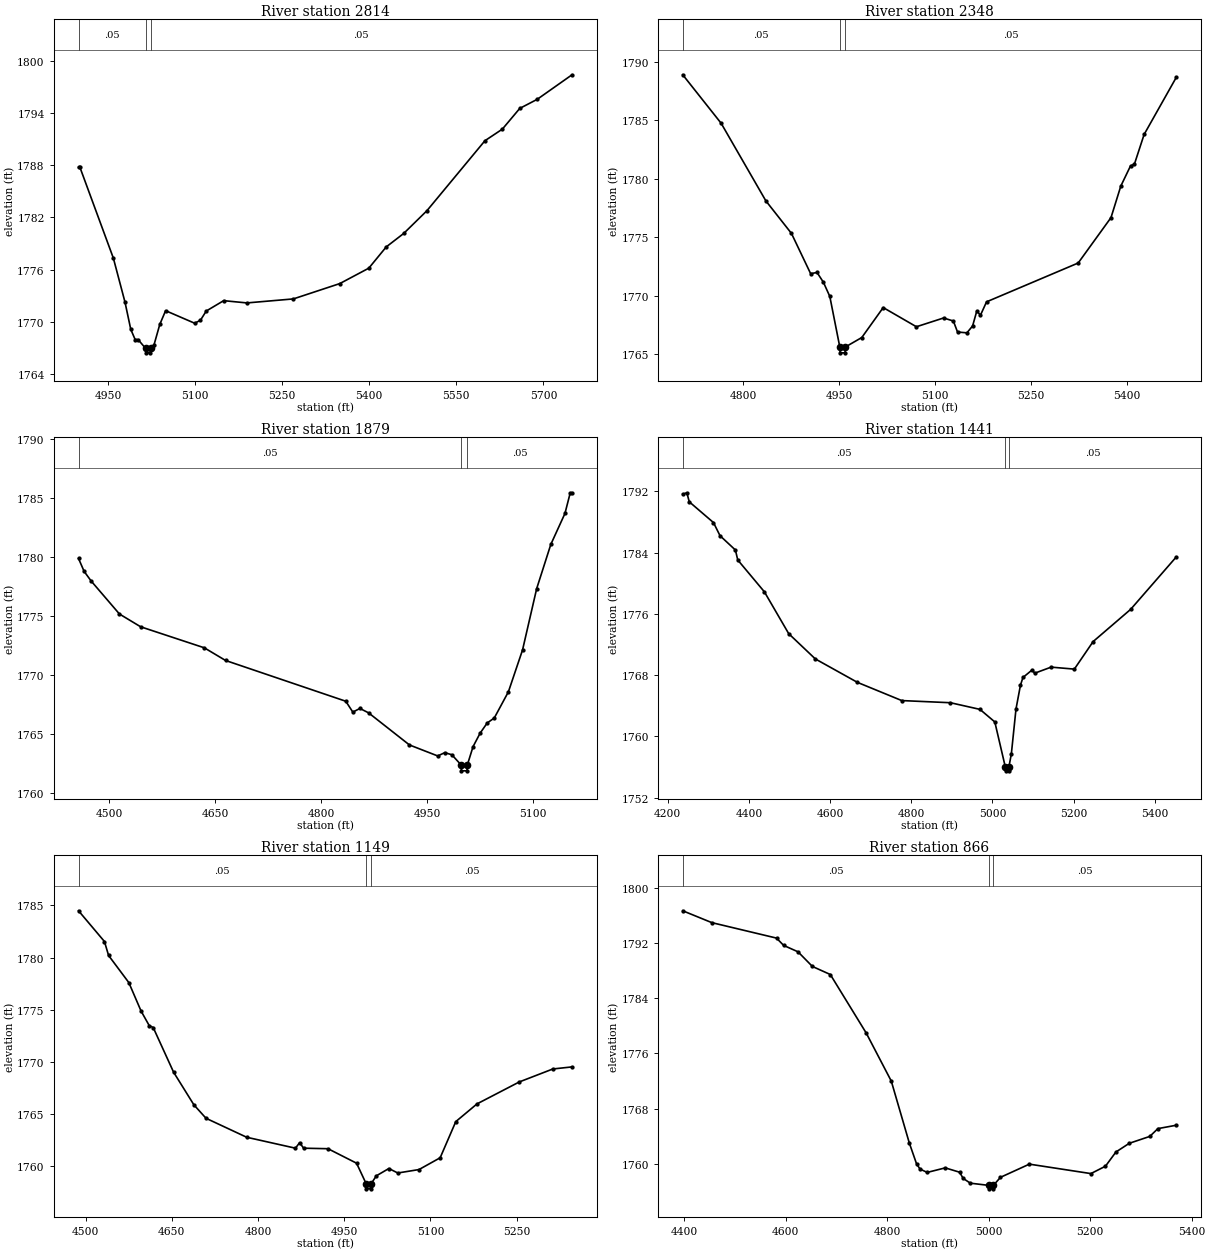
Type RM Length L Ch R = 1,2814,466,466,466
BEGIN DESCRIPTION:
Deadman 44 5.0
END DESCRIPTION:
XS GIS Cut Line= 3
      1641955.02      6890388.00      1642055.00      6890388.00
      1642805.02      6890388.00
#Sta/Elev= 30
  4899.2 1787.73  4901.7 1787.73  4959.2 1777.32  4979.2 1772.28  4989.2 1769.14
  4996.7 1767.98  5001.7 1767.98  5014.9 1766.95  5015.4 1766.45  5023.0 1766.45
  5023.5 1766.95  5029.2 1767.36  5039.2 1769.72  5049.2 1771.29  5099.2 1769.85
  5109.2 1770.19  5119.2 1771.25  5149.2 1772.44  5189.2 1772.18  5269.2 1772.64
  5349.2 1774.40  5399.2 1776.17  5429.2 1778.61  5459.2 1780.15  5499.2 1782.76
  5599.2 1790.80  5629.2 1792.13  5659.2 1794.51  5689.2 1795.55  5749.2 1798.37
#Mann=3,-1,0
  4899.2    0.05       0  5014.9    0.03       0  5023.5    0.05       0
Bank Sta=5014.9,5023.5
Exp/Cntr=0.3,0.1

Type RM Length L Ch R = 1,2348,469,469,469
BEGIN DESCRIPTION:
Deadman 44 4.0
END DESCRIPTION:
XS GIS Cut Line= 3
      1641955.04      6890788.00      1642255.00      6890788.00
      1642655.03      6890537.98
#Sta/Elev= 30
  4705.4 1788.90  4765.4 1784.76  4835.4 1778.12  4875.4 1775.34  4905.4 1771.90
  4915.4 1772.00  4925.4 1771.16  4935.4 1769.95  4951.0 1765.63  4951.5 1765.13
  4959.2 1765.13  4959.7 1765.63  4985.4 1766.44  5018.9 1769.00  5070.8 1767.36
  5113.3 1768.11  5128.6 1767.85  5135.1 1766.91  5149.8 1766.84  5158.7 1767.43
  5165.2 1768.70  5171.0 1768.35  5180.5 1769.49  5323.8 1772.81  5375.1 1776.69
  5390.4 1779.38  5405.7 1781.12  5411.6 1781.24  5426.9 1783.80  5477.1 1788.67
#Mann=3,-1,0
  4705.4    0.05       0  4951.0    0.03       0  4959.7    0.05       0
Bank Sta=4951,4959.7
Exp/Cntr=0.3,0.1

Type RM Length L Ch R = 1,1879,438,438,438
BEGIN DESCRIPTION:
Deadman 44 3.0
END DESCRIPTION:
XS GIS Cut Line= 3
      1642007.12      6891157.47      1642555.00      6891138.00
      1642704.97      6891138.00
#Sta/Elev= 30
  4457.0 1779.87  4464.9 1778.78  4474.9 1777.96  4514.9 1775.17  4544.9 1774.09
  4635.0 1772.31  4665.0 1771.24  4835.1 1767.79  4845.1 1766.87  4855.1 1767.18
  4867.3 1766.81  4925.2 1764.09  4965.2 1763.16  4975.2 1763.44  4985.2 1763.26
  4998.3 1762.40  4998.8 1761.90  5006.6 1761.90  5007.1 1762.40  5015.2 1763.95
  5025.2 1765.09  5035.2 1765.95  5045.2 1766.37  5065.2 1768.59  5085.2 1772.13
  5105.2 1777.32  5125.2 1781.06  5145.2 1783.68  5152.7 1785.43  5155.2 1785.43
#Mann=3,-1,0
  4457.0    0.05       0  4998.3    0.05       0  5007.1    0.05       0
Bank Sta=4998.3,5007.1
Exp/Cntr=0.3,0.1

Type RM Length L Ch R = 1,1441,292,292,292
BEGIN DESCRIPTION:
Deadman 44 2.0
END DESCRIPTION:
XS GIS Cut Line= 3
      1641820.87      6891138.36      1642492.02      6891501.73
      1642904.96      6891687.98
#Sta/Elev= 30
  4236.8 1791.63  4246.9 1791.82  4252.9 1790.64  4312.5 1787.93  4328.7 1786.21
  4366.6 1784.34  4372.4 1783.04  4438.0 1778.88  4498.0 1773.41  4563.6 1770.11
  4667.3 1767.05  4776.6 1764.67  4896.5 1764.39  4969.3 1763.52  5005.9 1761.88
  5031.8 1755.99  5032.3 1755.49  5040.1 1755.49  5040.6 1755.99  5046.7 1757.72
  5058.1 1763.57  5069.1 1766.68  5075.3 1767.69  5098.5 1768.70  5103.9 1768.24
  5144.7 1769.04  5201.9 1768.78  5248.2 1772.38  5340.7 1776.59  5453.0 1783.43
#Mann=3,-1,0
  4236.8    0.05       0  5031.8    0.03       0  5040.6    0.05       0
Bank Sta=5031.8,5040.6
Exp/Cntr=0.3,0.1

Type RM Length L Ch R = 1,1149,283,283,283
BEGIN DESCRIPTION:
Mapping XS 566ab111
END DESCRIPTION:
XS GIS Cut Line= 3
      1641905.54      6891333.69      1642278.80      6891693.93
      1642569.56      6891869.69
#Sta/Elev= 30
  4487.7 1784.49  4532.8 1781.54  4540.0 1780.20  4575.2 1777.60  4596.5 1774.87
  4610.7 1773.47  4617.6 1773.29  4653.1 1769.00  4688.4 1765.87  4709.5 1764.58
  4780.2 1762.76  4865.1 1761.71  4872.3 1762.24  4879.3 1761.71  4921.7 1761.66
  4971.4 1760.27  4988.0 1758.31  4988.5 1757.81  4996.4 1757.81  4996.9 1758.31
  5005.8 1759.06  5027.6 1759.76  5043.1 1759.33  5080.0 1759.66  5116.8 1760.79
  5144.0 1764.26  5180.9 1765.96  5254.6 1768.07  5312.8 1769.31  5346.2 1769.51
#Mann=3,-1,0
  4487.7    0.05       0  4988.0    0.03       0  4996.9    0.05       0
Bank Sta=4988,4996.9
Exp/Cntr=0.3,0.1

Type RM Length L Ch R = 1,866,281,281,281
BEGIN DESCRIPTION:
Mapping XS 493852d5
END DESCRIPTION:
XS GIS Cut Line= 3
      1641599.25      6891392.74      1642037.86      6891814.04
      1642389.88      6891906.38
#Sta/Elev= 30
  4397.4 1796.68  4454.7 1794.96  4582.1 1792.72  4596.2 1791.66  4624.5 1790.73
  4652.8 1788.61  4688.1 1787.44  4758.8 1778.96  4808.2 1771.99  4843.7 1763.02
  4857.9 1760.01  4864.8 1759.24  4878.9 1758.75  4914.5 1759.41  4942.8 1758.78
  4949.7 1757.89  4963.9 1757.19  5000.4 1756.87  5000.9 1756.37  5008.8 1756.37
  5009.3 1756.87  5023.3 1758.04  5080.2 1759.95  5201.4 1758.58  5230.1 1759.65
  5250.7 1761.71  5277.0 1762.97  5317.4 1763.97  5333.4 1765.10  5369.5 1765.59
#Mann=3,-1,0
  4397.4    0.05       0  5000.4    0.05       0  5009.3    0.05       0
Bank Sta=5000.4,5009.3
Exp/Cntr=0.3,0.1

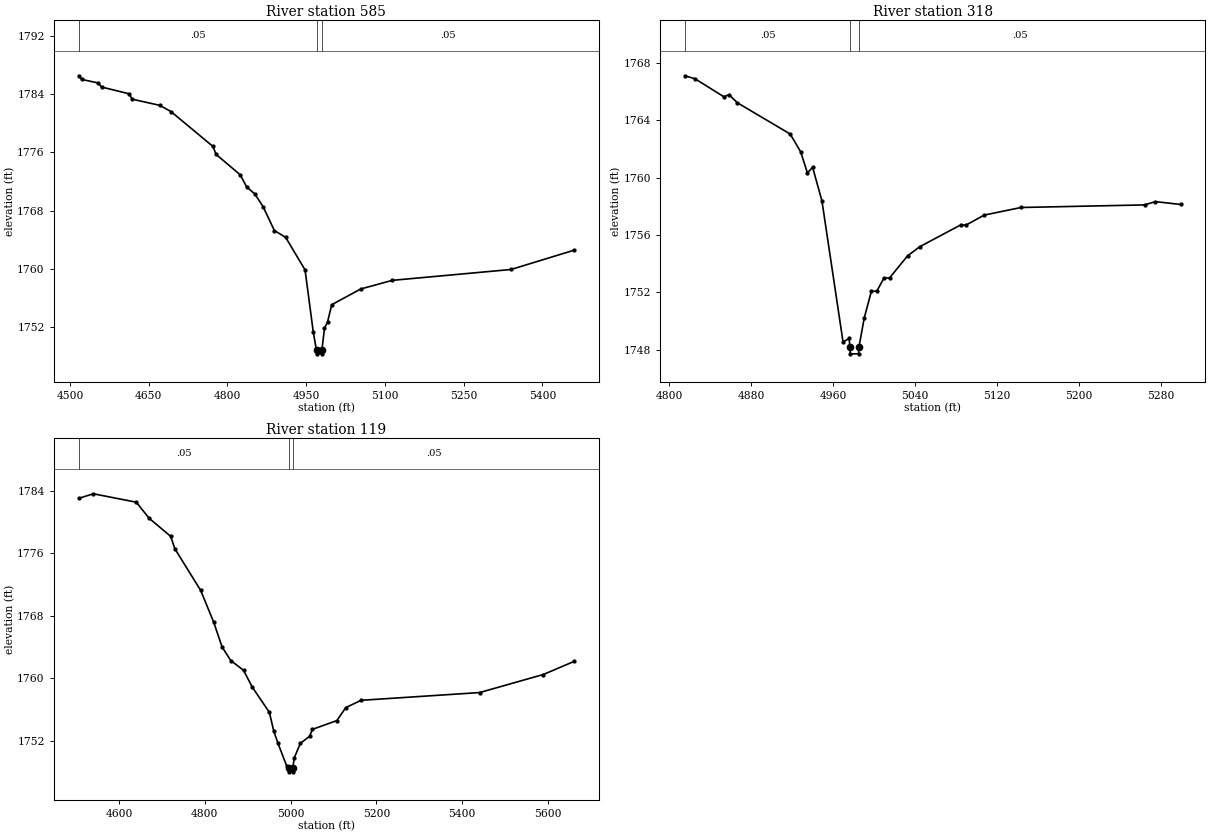
Type RM Length L Ch R = 1,585,267,267,267
BEGIN DESCRIPTION:
Mapping XS 91d29fa0
END DESCRIPTION:
XS GIS Cut Line= 4
      1641420.31      6891762.09      1641867.60      6892027.59
      1641983.03      6892027.59      1642288.89      6891987.19
#Sta/Elev= 30
  4516.5 1786.49  4523.0 1785.98  4554.2 1785.50  4560.1 1784.95  4612.7 1784.02
  4618.5 1783.28  4671.2 1782.43  4692.6 1781.57  4772.5 1776.79  4778.3 1775.71
  4824.3 1772.91  4836.7 1771.24  4852.4 1770.26  4868.0 1768.53  4889.4 1765.26
  4910.8 1764.34  4947.9 1759.86  4963.5 1751.36  4969.3 1748.96  4971.0 1748.85
  4971.5 1748.35  4979.5 1748.35  4980.0 1748.85  4984.9 1751.87  4990.7 1752.71
  4998.7 1755.09  5054.1 1757.25  5114.1 1758.43  5340.3 1759.92  5460.6 1762.57
#Mann=3,-1,0
  4516.5    0.05       0  4971.0    0.05       0  4980.0    0.05       0
Bank Sta=4971,4980
Exp/Cntr=0.3,0.1

Type RM Length L Ch R = 1,318,199,199,199
BEGIN DESCRIPTION:
Mapping XS 7c460c87
END DESCRIPTION:
XS GIS Cut Line= 3
      1641625.60      6892193.06      1641803.54      6892238.63
      1642076.98      6892114.94
#Sta/Elev= 30
  4815.4 1767.09  4825.1 1766.88  4853.2 1765.63  4858.3 1765.77  4866.4 1765.21
  4918.0 1763.03  4928.3 1761.78  4934.8 1760.32  4939.9 1760.71  4949.0 1758.37
  4969.6 1748.54  4975.6 1748.78  4976.2 1748.21  4976.7 1747.71  4984.7 1747.71
  4985.2 1748.21  4990.3 1750.21  4997.3 1752.08  5002.6 1752.08  5009.5 1752.99
  5015.0 1753.00  5032.6 1754.54  5044.6 1755.18  5084.3 1756.69  5089.8 1756.69
  5107.4 1757.38  5143.4 1757.91  5264.1 1758.09  5274.6 1758.32  5299.2 1758.12
#Mann=3,-1,0
  4815.4    0.05       0  4976.2    0.05       0  4985.2    0.05       0
Bank Sta=4976.2,4985.2
Exp/Cntr=0.3,0.1

Type RM Length L Ch R = 1,119,0,0,0
BEGIN DESCRIPTION:
Deadman 44 1.0
END DESCRIPTION:
XS GIS Cut Line= 3
      1641310.68      6892422.93      1641809.89      6892437.35
      1642257.17      6891958.33
#Sta/Elev= 30
  4505.9 1783.02  4540.2 1783.61  4640.3 1782.53  4670.3 1780.47  4720.3 1778.17
  4730.3 1776.56  4790.3 1771.25  4820.4 1767.22  4840.4 1763.99  4860.4 1762.28
  4890.4 1761.02  4910.4 1758.89  4950.4 1755.65  4960.4 1753.30  4970.4 1751.70
  4990.4 1748.84  4995.9 1748.54  4996.4 1748.04  5004.4 1748.04  5004.9 1748.54
  5008.4 1749.83  5022.5 1751.68  5044.0 1752.58  5050.9 1753.48  5107.5 1754.59
  5128.6 1756.26  5164.2 1757.19  5440.2 1758.18  5588.7 1760.49  5660.7 1762.17
#Mann=3,-1,0
  4505.9    0.05       0  4995.9    0.05       0  5004.9    0.05       0
Bank Sta=4995.9,5004.9
Exp/Cntr=0.3,0.1

Chan Stop Cuts=-1