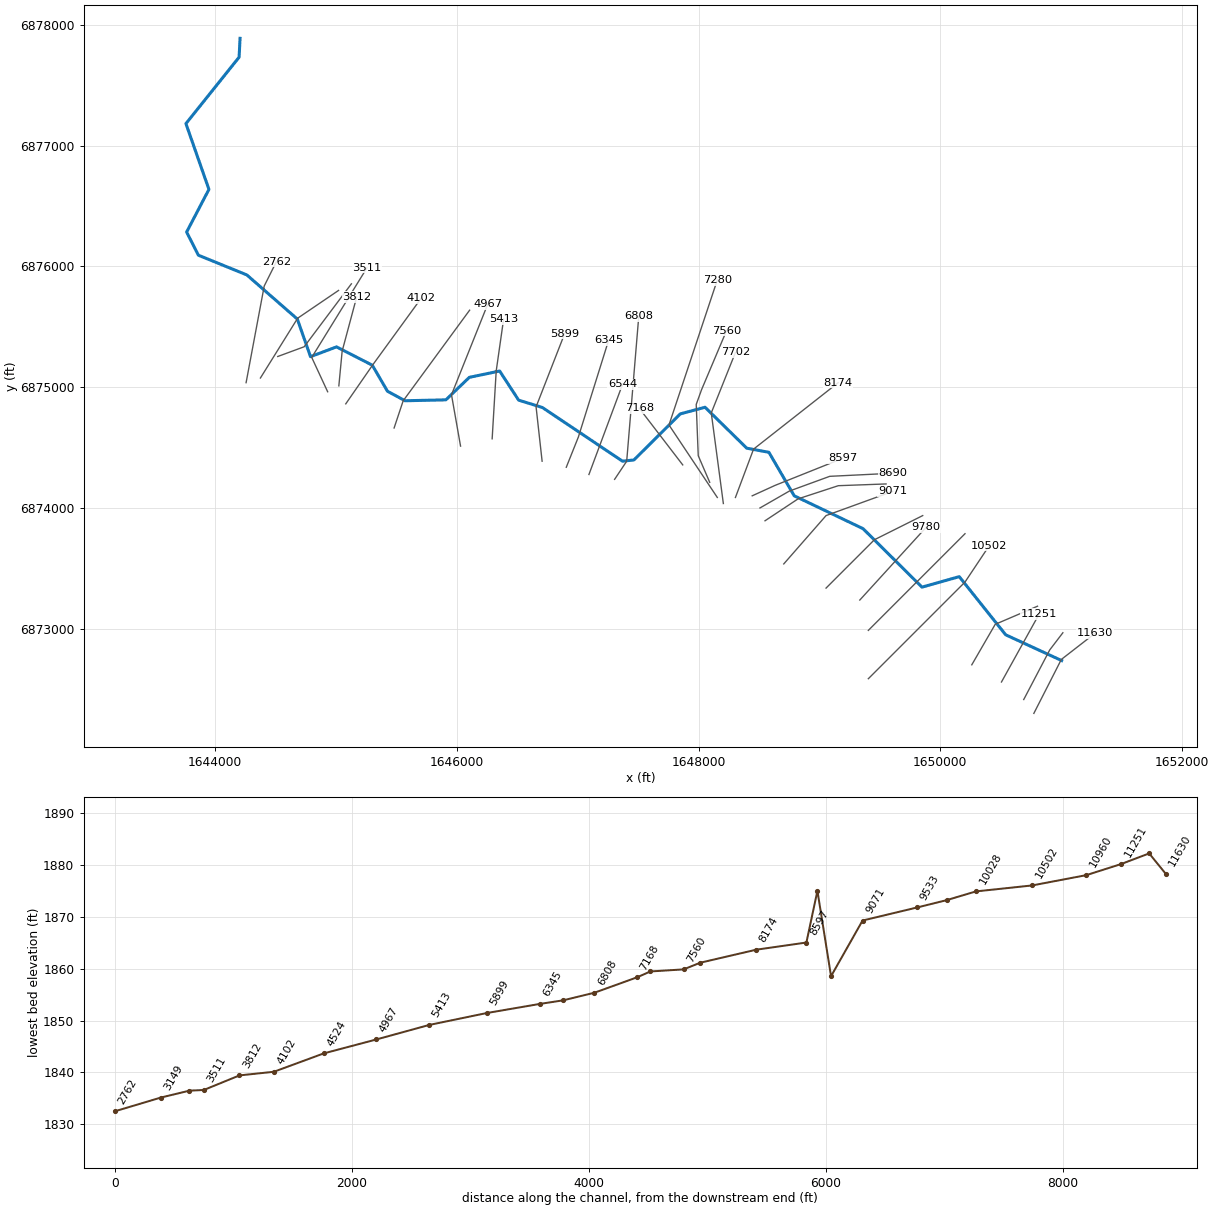
--- Deadman 46.prj (project) ---

Proj Title=Deadman 46 Base Level Engineering
Current Plan=p01
Default Exp/Contr=0.3,0.1
English Units
Geom File=g01
Flow File=f01
Plan File=p01
BEGIN DESCRIPTION:
Deadman 46
END DESCRIPTION:

--- Deadman 46.p01 (plan) ---

Plan Title=Multiple Run
Short Identifier=Multiple
Geom File=g01
Flow File=f01
Subcritical Flow
K Sum by GR= 0
Std Step Tol= 0.01
Critical Tol= 0.01
Num of Std Step Trials= 20
Max Error Tol= 0.3
Flow Tol Ratio= 0.001
Split Flow NTrial= 30
Split Flow Tol= 0.02
Split Flow Ratio= 0.02
Log Output Level= 0
Friction Slope Method= 1
Unsteady Friction Slope Method= 2
Unsteady Bridges Friction Slope Method= 1
Parabolic Critical Depth
Global Vel Dist=  1 , 1 , 1
Global Log Level= 0
CheckData=True
Encroach Param= -1, 0, 0, 0
BEGIN DESCRIPTION:
Multiple Run
END DESCRIPTION:

--- Deadman 46.f01 (steady flow) ---

Flow Title=Multiple
Number of Profiles=7
Profile Names=10-year,25-year,50-year,1pct_min,100-year,1pct_plu,500-year
River Rch & RM= Deadman 46,Reach-1,11630
     231     318     388     237     473     943     708
River Rch & RM= Deadman 46,Reach-1,11490
     310     431     531     326     651    1298     988
River Rch & RM= Deadman 46,Reach-1,3390
     546     783     984     615    1227    2448    1932
Boundary for River Rch & Prof#=Deadman 46,Reach-1,1
Up Type=0
Dn Type=3
Dn Slope=0.009
Boundary for River Rch & Prof#=Deadman 46,Reach-1,2
Up Type=0
Dn Type=3
Dn Slope=0.009
Boundary for River Rch & Prof#=Deadman 46,Reach-1,3
Up Type=0
Dn Type=3
Dn Slope=0.009
Boundary for River Rch & Prof#=Deadman 46,Reach-1,4
Up Type=0
Dn Type=3
Dn Slope=0.009
Boundary for River Rch & Prof#=Deadman 46,Reach-1,5
Up Type=0
Dn Type=3
Dn Slope=0.009
Boundary for River Rch & Prof#=Deadman 46,Reach-1,6
Up Type=0
Dn Type=3
Dn Slope=0.009
Boundary for River Rch & Prof#=Deadman 46,Reach-1,7
Up Type=0
Dn Type=3
Dn Slope=0.009

--- Deadman 46.g01 (geometry) ---

Geom Title=Existing Conditions

River Reach=Deadman 46,Reach-1
Reach XY= 30
      1651005.00      6872738.00      1650541.67      6872951.39
      1650157.43      6873432.60      1649848.83      6873345.76
      1649361.06      6873829.86      1648791.76      6874101.62
      1648581.93      6874461.86      1648398.81      6874495.82
      1648053.50      6874834.54      1647848.94      6874779.86
      1647464.79      6874398.43      1647370.27      6874388.36
      1646707.43      6874832.48      1646510.58      6874893.58
      1646353.54      6875134.48      1646102.70      6875082.17
      1645908.41      6874895.82      1645570.21      6874888.50
      1645424.68      6874967.68      1645299.56      6875182.75
      1645003.41      6875334.33      1644788.22      6875253.40
      1644678.83      6875564.87      1644261.05      6875929.84
      1643860.11      6876093.11      1643762.78      6876284.60
      1643947.44      6876638.00      1643757.05      6877182.14
      1644197.19      6877731.81      1644205.00      6877888.00

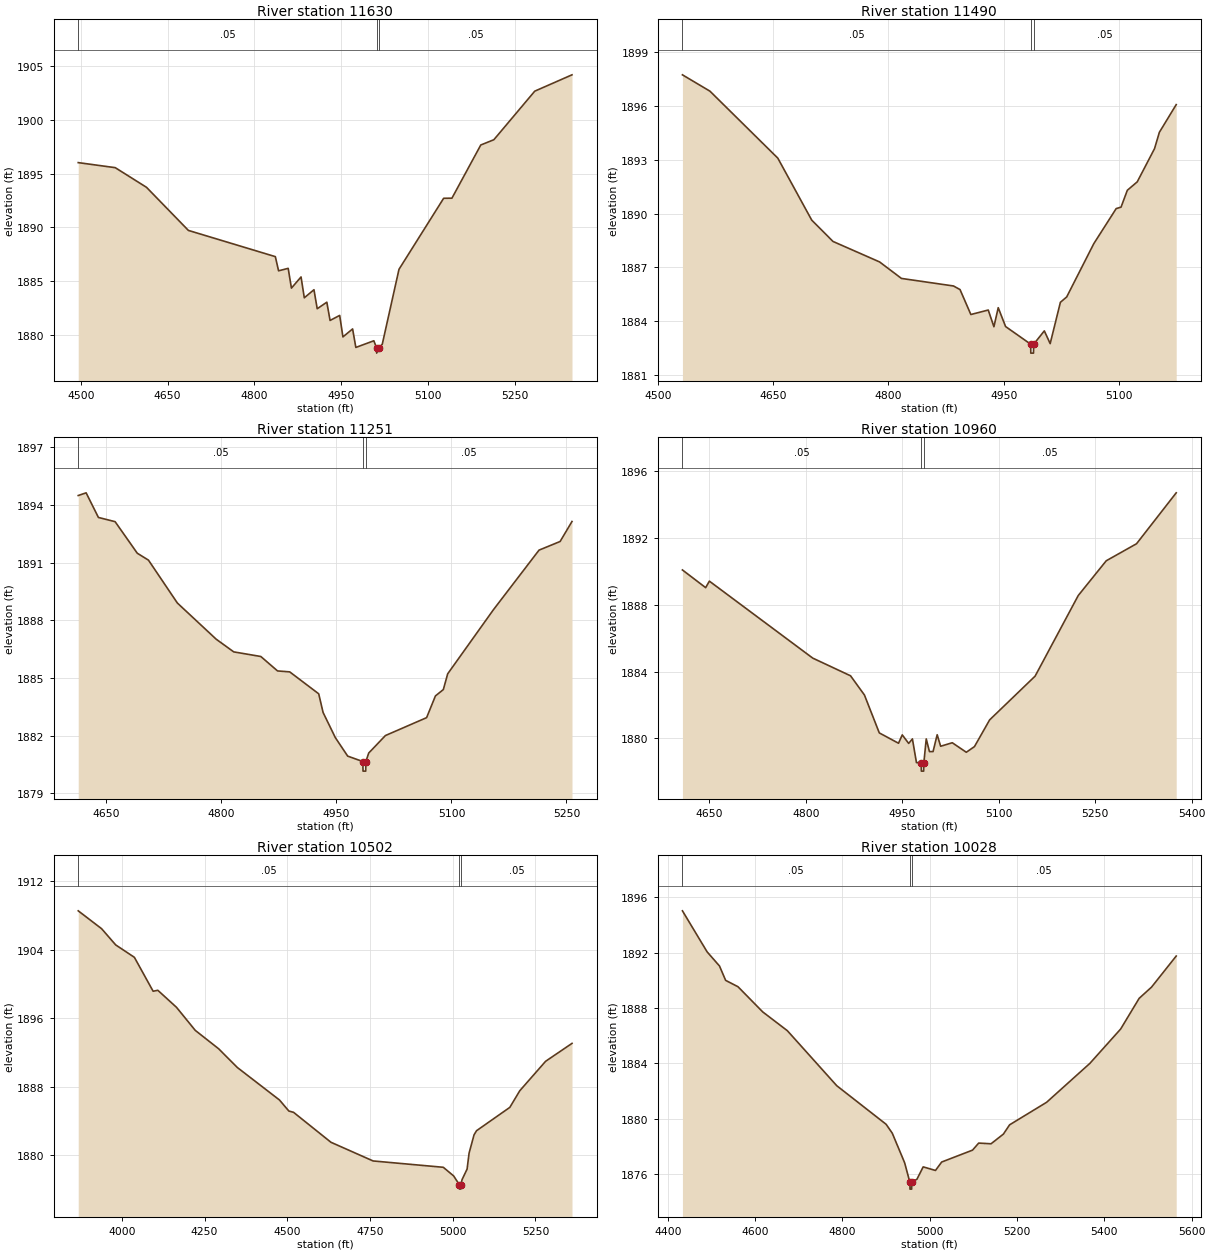
Type RM Length L Ch R = 1,11630,140,140,140
BEGIN DESCRIPTION:
Deadman 46 24.0
END DESCRIPTION:
XS GIS Cut Line= 3
      1650774.86      6872301.05      1651002.39      6872747.43
      1651280.00      6872963.00
#Sta/Elev= 30
  4495.7 1896.02  4559.6 1895.55  4613.6 1893.72  4685.9 1889.71  4836.0 1887.27
  4841.6 1885.95  4858.2 1886.18  4863.8 1884.34  4880.4 1885.38  4886.0 1883.44
  4902.7 1884.19  4908.3 1882.42  4924.9 1883.03  4930.5 1881.33  4947.1 1881.80
  4952.7 1879.80  4969.4 1880.54  4975.0 1878.82  5006.1 1879.44  5010.7 1878.79
  5010.9 1878.29  5014.7 1878.79  5020.6 1879.11  5049.5 1886.09  5126.6 1892.70
  5140.9 1892.71  5190.7 1897.66  5213.3 1898.15  5283.9 1902.67  5348.2 1904.19
#Mann=3,-1,0
  4495.7    0.05       0  5010.7    0.05       0  5014.7    0.05       0
Bank Sta=5010.7,5014.7
Exp/Cntr=0.3,0.1

Type RM Length L Ch R = 1,11490,239,239,239
BEGIN DESCRIPTION:
Mapping XS f7989f1f
END DESCRIPTION:
XS GIS Cut Line= 3
      1650691.13      6872415.55      1650906.08      6872825.91
      1651014.97      6872968.30
#Sta/Elev= 30
  4531.9 1897.73  4567.7 1896.82  4656.0 1893.09  4700.1 1889.64  4727.8 1888.45
  4788.4 1887.31  4816.9 1886.39  4884.6 1885.97  4893.1 1885.77  4907.2 1884.38
  4929.8 1884.63  4937.2 1883.70  4942.8 1884.76  4952.4 1883.71  4985.0 1882.73
  4985.2 1882.23  4988.7 1882.23  4989.0 1882.73  5002.8 1883.47  5010.4 1882.76
  5023.7 1885.06  5031.9 1885.36  5067.2 1888.33  5096.3 1890.28  5102.6 1890.36
  5110.8 1891.30  5123.7 1891.77  5146.2 1893.62  5152.5 1894.53  5174.4 1896.07
#Mann=3,-1,0
  4531.9    0.05       0  4985.0    0.03       0  4989.0    0.05       0
Bank Sta=4985,4989
Exp/Cntr=0.3,0.1

Type RM Length L Ch R = 1,11251,291,291,291
BEGIN DESCRIPTION:
Mapping XS 51fe6cd2
END DESCRIPTION:
XS GIS Cut Line= 2
      1650506.86      6872560.67      1650819.09      6873123.81
#Sta/Elev= 30
  4613.3 1894.49  4623.6 1894.63  4639.6 1893.35  4661.4 1893.13  4690.3 1891.49
  4704.9 1891.13  4742.6 1888.90  4793.2 1887.02  4816.1 1886.36  4851.4 1886.12
  4873.2 1885.37  4889.1 1885.32  4926.9 1884.18  4932.6 1883.21  4948.6 1881.90
  4964.7 1880.94  4984.4 1880.66  4984.7 1880.16  4988.2 1880.16  4988.4 1880.66
  4992.1 1881.10  5013.9 1882.01  5067.6 1882.94  5079.1 1884.07  5089.4 1884.40
  5095.1 1885.22  5154.7 1888.55  5214.2 1891.65  5241.7 1892.10  5257.2 1893.14
#Mann=3,-1,0
  4613.3    0.05       0  4984.4    0.03       0  4988.4    0.05       0
Bank Sta=4984.4,4988.4
Exp/Cntr=0.3,0.1

Type RM Length L Ch R = 1,10960,458,458,458
BEGIN DESCRIPTION:
Deadman 46 23.0
END DESCRIPTION:
XS GIS Cut Line= 3
      1650261.19      6872703.04      1650455.00      6873038.00
      1650805.02      6873188.01
#Sta/Elev= 30
  4608.2 1890.09  4644.3 1889.03  4650.1 1889.42  4810.8 1884.81  4869.6 1883.75
  4891.2 1882.60  4914.3 1880.33  4944.2 1879.71  4950.0 1880.21  4960.0 1879.70
  4965.8 1879.97  4972.1 1878.55  4979.5 1878.54  4979.7 1878.04  4983.3 1878.04
  4983.6 1878.54  4987.3 1879.97  4992.3 1879.21  4997.9 1879.21  5004.3 1880.22
  5009.7 1879.53  5027.8 1879.74  5049.6 1879.17  5062.3 1879.51  5085.9 1881.11
  5156.6 1883.73  5223.7 1888.56  5267.2 1890.64  5314.3 1891.66  5376.0 1894.71
#Mann=3,-1,0
  4608.2    0.05       0  4979.5    0.03       0  4983.6    0.05       0
Bank Sta=4979.5,4983.6
Exp/Cntr=0.3,0.1

Type RM Length L Ch R = 1,10502,474,474,474
BEGIN DESCRIPTION:
Deadman 46 22.0
END DESCRIPTION:
XS GIS Cut Line= 3
      1649404.98      6872587.98      1650205.00      6873388.00
      1650405.02      6873688.03
#Sta/Elev= 30
  3868.4 1908.55  3939.1 1906.46  3981.6 1904.57  4038.1 1903.12  4094.7 1899.16
  4108.9 1899.27  4165.4 1897.28  4222.0 1894.59  4292.7 1892.44  4349.3 1890.25
  4476.5 1886.46  4504.8 1885.17  4519.0 1885.02  4632.1 1881.52  4759.4 1879.34
  4971.5 1878.60  5002.8 1877.59  5020.3 1876.55  5020.5 1876.05  5024.1 1876.05
  5024.4 1876.55  5028.3 1877.17  5043.4 1878.39  5049.4 1880.25  5064.4 1882.39
  5071.9 1882.87  5172.6 1885.60  5202.6 1887.54  5280.7 1890.98  5360.4 1893.07
#Mann=3,-1,0
  3868.4    0.05       0  5020.3    0.03       0  5024.4    0.05       0
Bank Sta=5020.3,5024.4
Exp/Cntr=0.3,0.1

Type RM Length L Ch R = 1,10028,248,248,248
BEGIN DESCRIPTION:
Deadman 46 21.0
END DESCRIPTION:
XS GIS Cut Line= 3
      1649404.98      6872987.98      1649805.00      6873388.00
      1650205.00      6873788.00
#Sta/Elev= 30
  4433.4 1895.03  4490.0 1892.06  4518.3 1891.04  4532.4 1890.00  4560.7 1889.54
  4617.3 1887.72  4673.8 1886.36  4787.0 1882.38  4900.1 1879.59  4914.3 1878.94
  4942.5 1876.81  4954.5 1875.40  4954.8 1874.90  4958.6 1874.90  4958.8 1875.40
  4970.8 1875.62  4985.0 1876.51  5013.2 1876.25  5027.4 1876.86  5098.1 1877.72
  5112.2 1878.23  5140.5 1878.18  5168.8 1878.88  5183.0 1879.55  5267.8 1881.18
  5366.8 1883.99  5437.5 1886.48  5479.9 1888.70  5508.2 1889.51  5564.8 1891.76
#Mann=3,-1,0
  4433.4    0.05       0  4954.5    0.03       0  4958.8    0.05       0
Bank Sta=4954.5,4958.8
Exp/Cntr=0.3,0.1

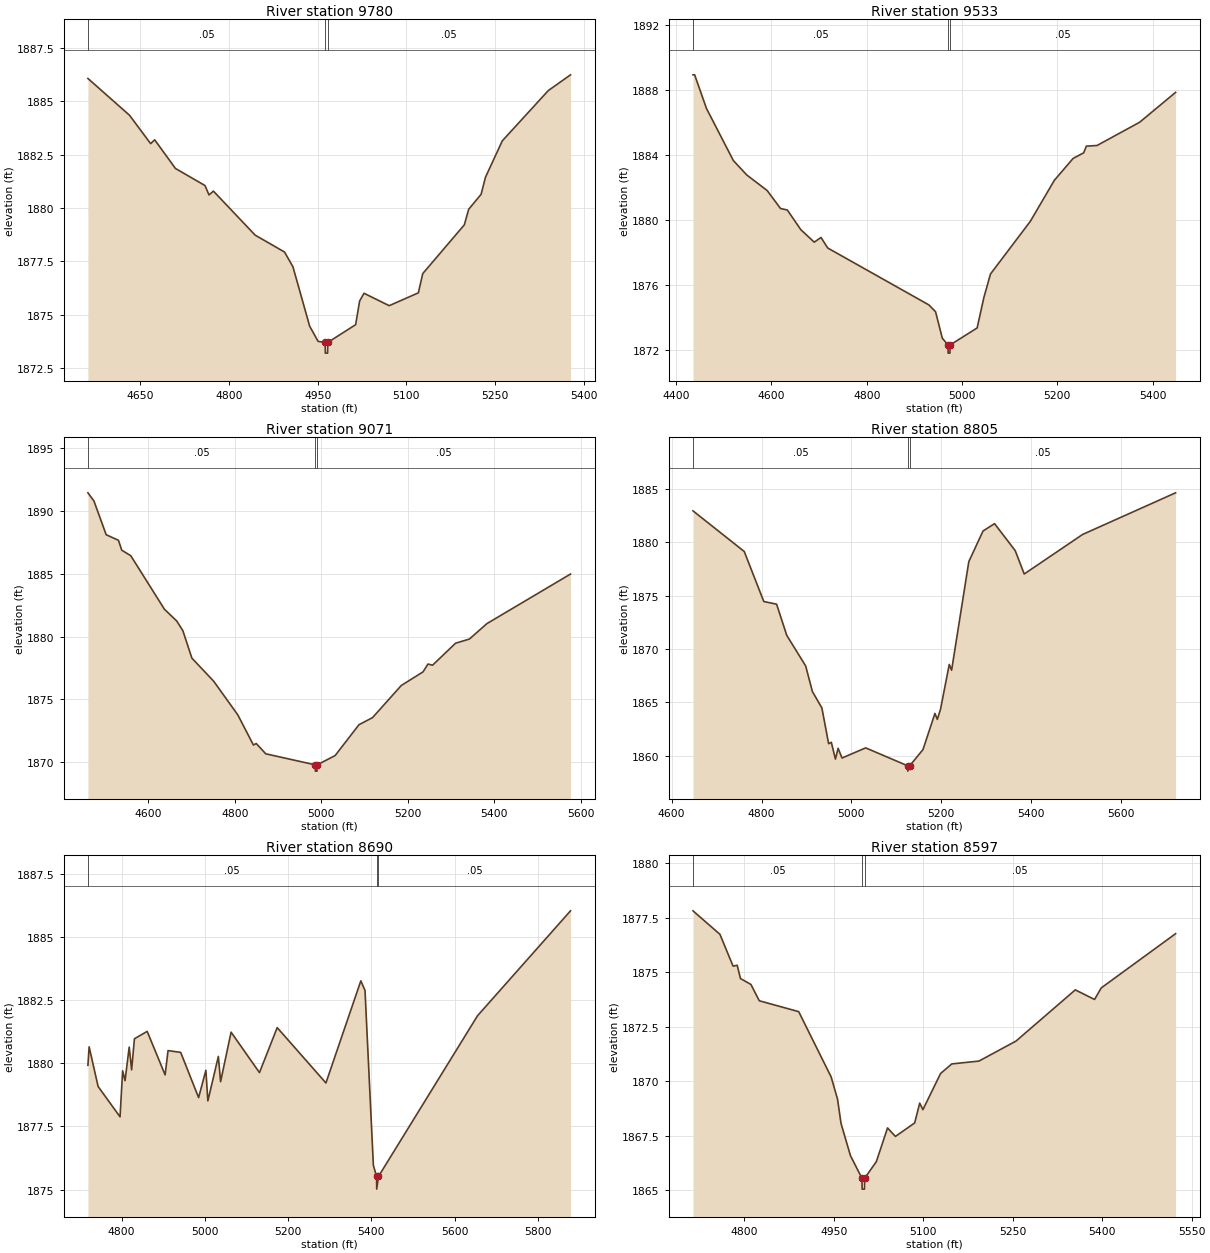
Type RM Length L Ch R = 1,9780,247,247,247
BEGIN DESCRIPTION:
Mapping XS b69df503
END DESCRIPTION:
XS GIS Cut Line= 2
      1649334.39      6873239.07      1649884.33      6873842.05
#Sta/Elev= 30
  4561.5 1886.06  4631.8 1884.34  4667.6 1883.01  4674.4 1883.19  4709.5 1881.85
  4759.5 1881.05  4766.3 1880.61  4773.7 1880.79  4844.3 1878.73  4894.0 1877.94
  4908.2 1877.25  4936.5 1874.47  4950.7 1873.76  4962.7 1873.71  4963.0 1873.21
  4966.8 1873.21  4967.1 1873.71  5014.2 1874.54  5021.0 1875.65  5028.4 1876.01
  5071.0 1875.43  5120.3 1876.03  5127.7 1876.93  5198.0 1879.21  5205.4 1879.94
  5226.4 1880.64  5233.8 1881.44  5262.2 1883.14  5339.9 1885.49  5377.6 1886.23
#Mann=3,-1,0
  4561.5    0.05       0  4962.7    0.05       0  4967.1    0.05       0
Bank Sta=4962.7,4967.1
Exp/Cntr=0.3,0.1

Type RM Length L Ch R = 1,9533,462,462,462
BEGIN DESCRIPTION:
Deadman 46 20.0
END DESCRIPTION:
XS GIS Cut Line= 3
      1649055.01      6873338.01      1649455.00      6873738.00
      1649855.01      6873938.00
#Sta/Elev= 30
  4435.3 1888.94  4438.8 1888.94  4463.6 1886.87  4520.1 1883.66  4548.4 1882.77
  4590.9 1881.82  4619.1 1880.71  4633.3 1880.62  4661.6 1879.41  4689.8 1878.64
  4704.0 1878.93  4718.1 1878.28  4930.3 1874.78  4944.4 1874.36  4958.6 1872.73
  4970.5 1872.31  4970.8 1871.81  4974.6 1871.81  4974.9 1872.31  5031.7 1873.36
  5045.7 1875.22  5059.7 1876.68  5143.5 1879.93  5193.8 1882.45  5233.0 1883.79
  5255.3 1884.14  5260.9 1884.55  5283.3 1884.59  5372.7 1886.02  5448.2 1887.86
#Mann=3,-1,0
  4435.3    0.05       0  4970.5    0.05       0  4974.9    0.05       0
Bank Sta=4970.5,4974.9
Exp/Cntr=0.3,0.1

Type RM Length L Ch R = 1,9071,266,266,266
BEGIN DESCRIPTION:
Deadman 46 19.0
END DESCRIPTION:
XS GIS Cut Line= 3
      1648704.98      6873537.97      1649055.00      6873938.00
      1649605.02      6874138.01
#Sta/Elev= 30
  4460.0 1891.45  4473.8 1890.81  4502.3 1888.11  4530.7 1887.67  4538.3 1886.88
  4559.2 1886.44  4637.0 1882.18  4665.5 1881.24  4679.8 1880.46  4700.6 1878.28
  4750.9 1876.45  4806.9 1873.76  4843.0 1871.36  4849.6 1871.48  4871.5 1870.66
  4986.0 1869.78  4986.3 1869.28  4990.2 1869.28  4990.5 1869.78  5032.1 1870.52
  5087.3 1872.98  5118.6 1873.54  5185.1 1876.10  5235.6 1877.19  5246.9 1877.81
  5257.6 1877.72  5310.8 1879.47  5342.7 1879.80  5383.3 1881.03  5576.8 1884.98
#Mann=3,-1,0
  4460.0    0.05       0  4986.0    0.05       0  4990.5    0.05       0
Bank Sta=4986,4990.5
Exp/Cntr=0.3,0.1

Type RM Length L Ch R = 1,8805,115,115,115
BEGIN DESCRIPTION:
Mapping XS 88c160df
END DESCRIPTION:
XS GIS Cut Line= 4
      1648549.93      6873895.10      1648823.52      6874076.56
      1649156.39      6874185.46      1649551.70      6874199.94
#Sta/Elev= 30
  4647.5 1882.94  4761.6 1879.13  4805.1 1874.44  4833.6 1874.19  4856.2 1871.27
  4898.3 1868.40  4913.3 1866.00  4934.4 1864.46  4949.4 1861.11  4955.4 1861.24
  4964.5 1859.67  4970.5 1860.68  4979.2 1859.77  5031.9 1860.72  5125.3 1859.04
  5125.6 1858.54  5129.8 1859.04  5159.4 1860.56  5186.0 1863.95  5191.3 1863.39
  5198.3 1864.32  5217.9 1868.54  5223.1 1868.00  5261.4 1878.18  5293.0 1881.05
  5318.7 1881.74  5364.7 1879.21  5384.7 1877.02  5514.8 1880.73  5721.6 1884.63
#Mann=3,-1,0
  4647.5    0.05       0  5125.3    0.03       0  5129.8    0.05       0
Bank Sta=5125.3,5129.8
Exp/Cntr=0.3,0.1

Type RM Length L Ch R = 1,8690,93,93,93
BEGIN DESCRIPTION:
Deadman 46 18.0
END DESCRIPTION:
XS GIS Cut Line= 4
      1648508.06      6874001.18      1648750.93      6874140.77
      1649085.52      6874262.95      1649608.17      6874288.55
#Sta/Elev= 30
  4719.1 1879.92  4722.0 1880.65  4743.6 1879.08  4796.3 1877.88  4802.5 1879.70
  4808.3 1879.31  4818.3 1880.64  4824.1 1879.74  4830.9 1880.97  4861.5 1881.26
  4904.6 1879.54  4911.6 1880.50  4942.0 1880.43  4985.1 1878.64  5002.5 1879.72
  5007.3 1878.51  5032.5 1880.27  5037.9 1879.27  5063.1 1881.23  5131.3 1879.63
  5173.9 1881.41  5291.0 1879.22  5374.9 1883.26  5384.9 1882.88  5405.0 1875.96
  5412.7 1875.52  5413.0 1875.02  5417.2 1875.52  5655.3 1881.88  5878.7 1886.03
#Mann=3,-1,0
  4719.1    0.05       0  5412.7    0.03       0  5417.2    0.05       0
Bank Sta=5412.7,5417.2
Exp/Cntr=0.3,0.1

Type RM Length L Ch R = 1,8597,423,423,423
BEGIN DESCRIPTION:
Mapping XS 046133ee
END DESCRIPTION:
XS GIS Cut Line= 3
      1648443.87      6874101.69      1648633.69      6874188.22
      1649191.04      6874411.17
#Sta/Elev= 30
  4714.2 1877.82  4759.4 1876.74  4781.4 1875.28  4788.3 1875.32  4793.8 1874.71
  4811.3 1874.44  4825.3 1873.69  4891.4 1873.19  4945.8 1870.19  4956.5 1869.17
  4962.3 1868.06  4978.1 1866.58  4997.4 1865.54  4997.7 1865.04  5001.6 1865.04
  5001.9 1865.54  5021.5 1866.30  5040.3 1867.85  5053.5 1867.46  5085.8 1868.08
  5094.2 1868.99  5099.6 1868.69  5129.2 1870.35  5148.0 1870.79  5193.5 1870.92
  5255.7 1871.84  5355.0 1874.19  5387.3 1873.75  5398.5 1874.28  5523.1 1876.77
#Mann=3,-1,0
  4714.2    0.05       0  4997.4    0.03       0  5001.9    0.05       0
Bank Sta=4997.4,5001.9
Exp/Cntr=0.3,0.1

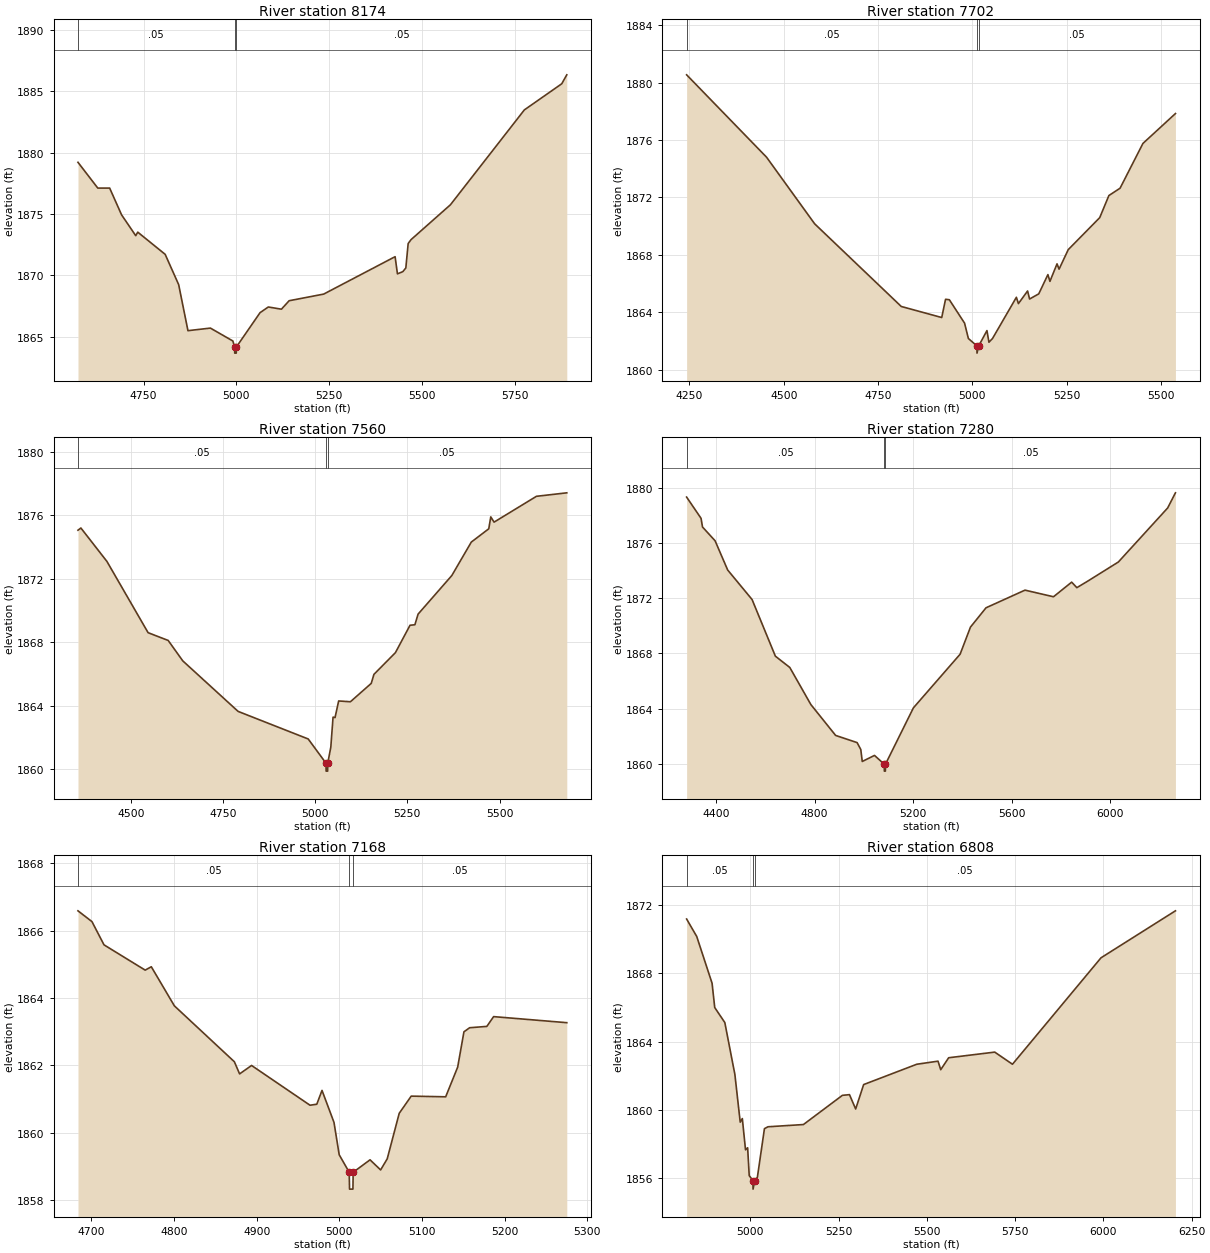
Type RM Length L Ch R = 1,8174,472,472,472
BEGIN DESCRIPTION:
Deadman 46 17.0
END DESCRIPTION:
XS GIS Cut Line= 3
      1648305.00      6874088.00      1648455.00      6874488.00
      1649154.98      6875037.98
#Sta/Elev= 30
  4573.1 1879.21  4626.5 1877.11  4658.5 1877.11  4690.6 1874.93  4728.8 1873.23
  4734.2 1873.52  4808.1 1871.71  4844.5 1869.24  4869.5 1865.49  4930.0 1865.70
  4990.5 1864.65  4995.3 1864.16  4995.6 1863.66  4999.6 1863.66  5000.0 1864.16
  5063.9 1866.96  5086.1 1867.42  5121.4 1867.24  5142.2 1867.93  5235.3 1868.47
  5427.8 1871.52  5434.1 1870.12  5448.6 1870.30  5456.7 1870.60  5463.0 1872.59
  5470.8 1872.91  5576.9 1875.75  5776.1 1883.48  5876.9 1885.61  5890.5 1886.34
#Mann=3,-1,0
  4573.1    0.05       0  4995.3    0.05       0  5000.0    0.05       0
Bank Sta=4995.3,5000
Exp/Cntr=0.3,0.1

Type RM Length L Ch R = 1,7702,142,142,142
BEGIN DESCRIPTION:
Deadman 46 16.0
END DESCRIPTION:
XS GIS Cut Line= 3
      1648205.00      6874038.02      1648105.00      6874788.00
      1648304.99      6875287.97
#Sta/Elev= 30
  4242.8 1880.54  4454.6 1874.80  4582.0 1870.16  4811.5 1864.40  4918.7 1863.63
  4928.8 1864.90  4938.9 1864.87  4979.2 1863.24  4989.3 1862.17  5011.9 1861.65
  5012.2 1861.15  5016.6 1861.65  5038.5 1862.72  5043.8 1861.91  5053.3 1862.17
  5116.5 1865.04  5121.9 1864.60  5146.2 1865.48  5151.5 1864.92  5175.8 1865.28
  5200.0 1866.62  5205.4 1866.15  5224.2 1867.37  5229.6 1867.00  5253.9 1868.36
  5337.3 1870.59  5361.6 1872.13  5391.2 1872.64  5451.8 1875.76  5537.9 1877.84
#Mann=3,-1,0
  4242.8    0.05       0  5011.9    0.05       0  5016.6    0.05       0
Bank Sta=5011.9,5016.6
Exp/Cntr=0.3,0.1

Type RM Length L Ch R = 1,7560,280,280,280
BEGIN DESCRIPTION:
Mapping XS 79d307a4
END DESCRIPTION:
XS GIS Cut Line= 5
      1648092.11      6874213.33      1647997.19      6874433.89
      1647980.44      6874858.22      1648025.11      6874981.05
      1648231.69      6875469.59
#Sta/Elev= 30
  4356.6 1875.07  4364.5 1875.21  4435.1 1873.10  4546.8 1868.60  4601.3 1868.11
  4640.9 1866.82  4791.0 1863.63  4981.1 1861.89  5029.4 1860.36  5029.7 1859.86
  5033.8 1859.86  5034.1 1860.36  5042.4 1861.37  5048.5 1863.27  5053.9 1863.24
  5063.7 1864.29  5095.6 1864.24  5152.1 1865.40  5159.4 1865.97  5217.7 1867.34
  5257.3 1869.07  5270.5 1869.10  5279.1 1869.77  5370.7 1872.21  5423.5 1874.32
  5470.9 1875.16  5476.3 1875.91  5485.3 1875.58  5600.2 1877.21  5682.5 1877.43
#Mann=3,-1,0
  4356.6    0.05       0  5029.4    0.05       0  5034.1    0.05       0
Bank Sta=5029.4,5034.1
Exp/Cntr=0.3,0.1

Type RM Length L Ch R = 1,7280,112,112,112
BEGIN DESCRIPTION:
Deadman 46 15.0
END DESCRIPTION:
XS GIS Cut Line= 3
      1648155.01      6874087.99      1647755.00      6874688.00
      1648154.99      6875887.97
#Sta/Elev= 30
  4279.9 1879.34  4338.5 1877.80  4344.5 1877.17  4395.6 1876.17  4446.7 1874.05
  4545.8 1871.91  4640.5 1867.80  4699.1 1866.98  4784.7 1864.29  4885.3 1862.05
  4972.5 1861.53  4987.5 1861.03  4993.5 1860.16  5043.2 1860.60  5083.0 1859.96
  5083.3 1859.46  5087.4 1859.46  5087.8 1859.96  5201.3 1864.05  5391.0 1867.94
  5433.2 1869.91  5496.4 1871.31  5654.6 1872.59  5770.5 1872.11  5844.3 1873.17
  5865.4 1872.77  5907.5 1873.22  6034.0 1874.63  6234.3 1878.55  6265.9 1879.65
#Mann=3,-1,0
  4279.9    0.05       0  5083.0    0.03       0  5087.8    0.05       0
Bank Sta=5083,5087.8
Exp/Cntr=0.3,0.1

Type RM Length L Ch R = 1,7168,360,360,360
BEGIN DESCRIPTION:
Mapping XS 31db13bd
END DESCRIPTION:
XS GIS Cut Line= 2
      1647868.81      6874357.60      1647508.82      6874826.69
#Sta/Elev= 30
  4683.8 1866.59  4700.7 1866.27  4715.3 1865.58  4765.1 1864.83  4772.5 1864.93
  4800.4 1863.77  4873.0 1862.11  4879.3 1861.75  4893.8 1862.00  4964.5 1860.82
  4972.7 1860.85  4979.0 1861.26  4993.5 1860.31  4999.8 1859.35  5011.9 1858.83
  5012.3 1858.33  5016.4 1858.33  5016.7 1858.83  5037.1 1859.20  5049.9 1858.90
  5057.9 1859.23  5072.4 1860.58  5086.9 1861.09  5128.6 1861.07  5143.1 1861.95
  5150.7 1863.00  5157.6 1863.12  5178.4 1863.16  5186.6 1863.45  5275.1 1863.27
#Mann=3,-1,0
  4683.8    0.05       0  5011.9    0.03       0  5016.7    0.05       0
Bank Sta=5011.9,5016.7
Exp/Cntr=0.3,0.1

Type RM Length L Ch R = 1,6808,264,264,264
BEGIN DESCRIPTION:
Deadman 46 14.0
END DESCRIPTION:
XS GIS Cut Line= 3
      1647304.99      6874237.98      1647405.00      6874388.00
      1647505.00      6875588.04
#Sta/Elev= 30
  4819.4 1871.17  4848.0 1870.15  4891.5 1867.41  4899.0 1865.99  4927.6 1865.11
  4956.1 1862.07  4971.2 1859.28  4977.2 1859.49  4986.2 1857.66  4992.2 1857.78
  4996.7 1856.15  5007.3 1855.86  5007.6 1855.36  5012.2 1855.86  5019.8 1856.05
  5039.8 1858.90  5049.9 1859.01  5150.2 1859.14  5260.6 1860.85  5280.7 1860.89
  5298.2 1860.05  5320.8 1861.48  5471.3 1862.67  5531.5 1862.85  5539.1 1862.35
  5561.6 1863.05  5692.1 1863.38  5742.3 1862.67  5993.1 1868.90  6203.9 1871.65
#Mann=3,-1,0
  4819.4    0.05       0  5007.3    0.05       0  5012.2    0.05       0
Bank Sta=5007.3,5012.2
Exp/Cntr=0.3,0.1

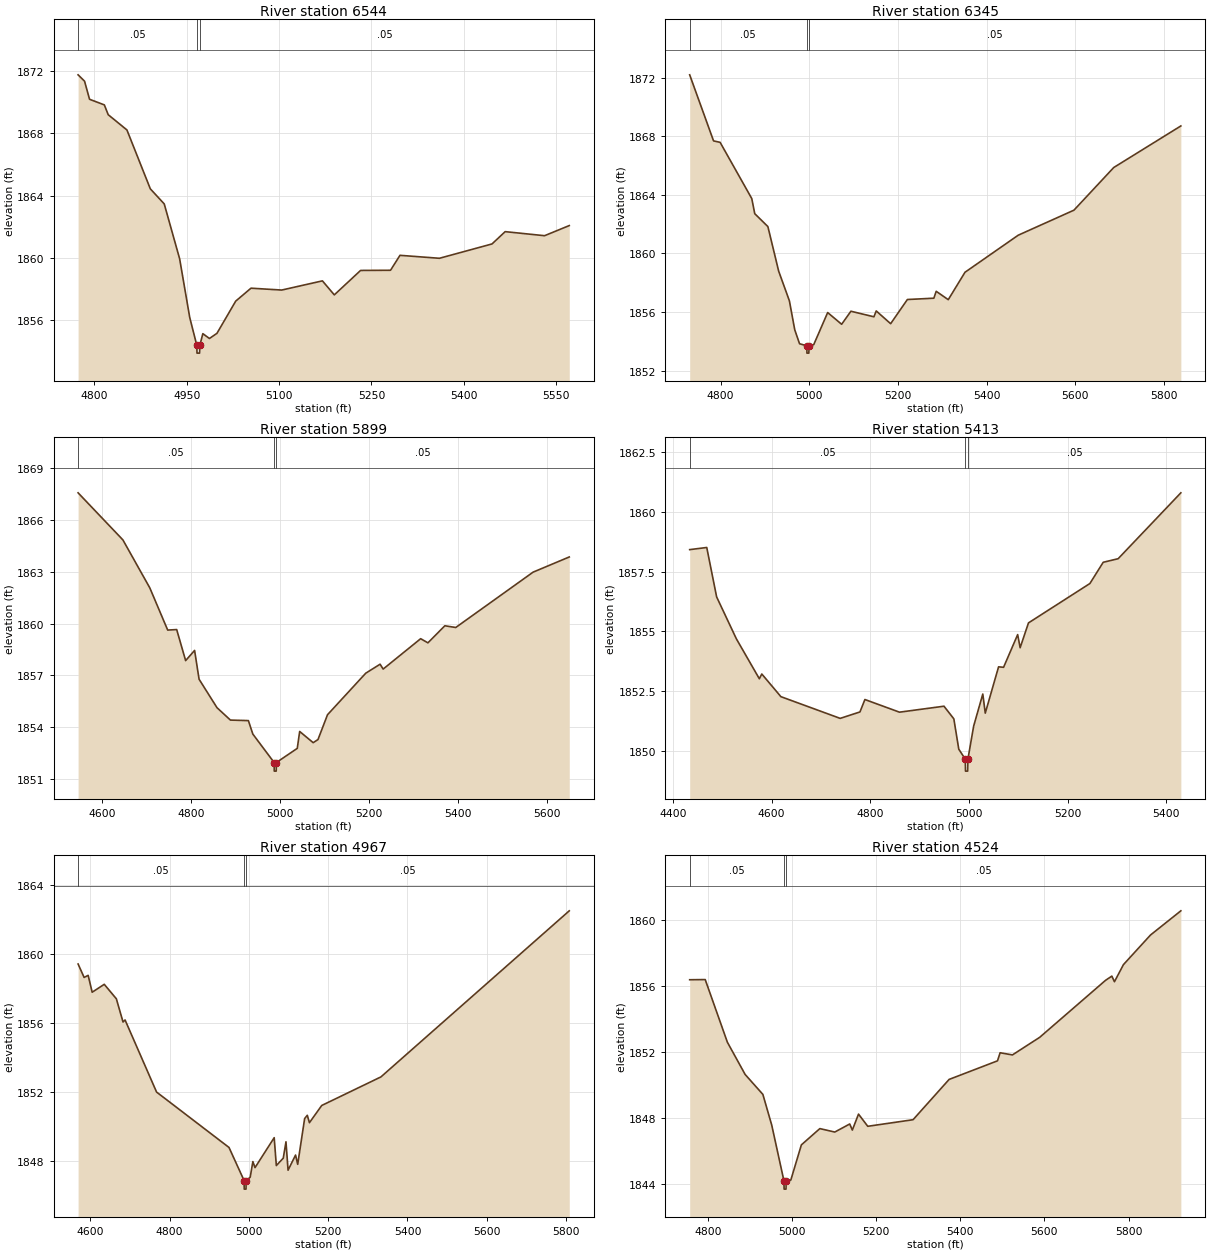
Type RM Length L Ch R = 1,6544,199,199,199
BEGIN DESCRIPTION:
Mapping XS f888219b
END DESCRIPTION:
XS GIS Cut Line= 2
      1647092.54      6874278.12      1647371.20      6875025.57
#Sta/Elev= 30
  4773.6 1871.76  4784.1 1871.35  4792.2 1870.19  4816.2 1869.83  4822.5 1869.20
  4852.9 1868.22  4890.9 1864.44  4913.5 1863.47  4938.5 1859.95  4954.9 1856.18
  4966.4 1854.39  4966.7 1853.89  4970.9 1853.89  4971.3 1854.39  4976.2 1855.14
  4986.9 1854.83  4999.1 1855.16  5029.6 1857.23  5054.4 1858.06  5104.3 1857.94
  5170.4 1858.53  5189.7 1857.63  5232.4 1859.20  5281.0 1859.21  5296.4 1860.17
  5360.4 1859.98  5445.8 1860.90  5467.2 1861.69  5531.2 1861.43  5571.3 1862.08
#Mann=3,-1,0
  4773.6    0.05       0  4966.4    0.05       0  4971.3    0.05       0
Bank Sta=4966.4,4971.3
Exp/Cntr=0.3,0.1

Type RM Length L Ch R = 1,6345,446,446,446
BEGIN DESCRIPTION:
Deadman 46 13.0
END DESCRIPTION:
XS GIS Cut Line= 3
      1646905.01      6874338.04      1647005.00      6874588.00
      1647255.01      6875388.03
#Sta/Elev= 30
  4730.3 1872.19  4784.1 1867.68  4798.9 1867.58  4870.3 1863.74  4877.0 1862.71
  4906.6 1861.83  4930.9 1858.79  4955.1 1856.76  4967.2 1854.78  4978.0 1853.83
  4994.4 1853.69  4994.7 1853.19  4998.9 1853.19  4999.3 1853.69  5010.0 1853.77
  5041.4 1855.96  5072.9 1855.16  5093.8 1856.05  5145.7 1855.67  5150.9 1856.07
  5183.4 1855.20  5221.1 1856.85  5280.8 1856.94  5286.1 1857.41  5313.3 1856.84
  5351.0 1858.71  5471.0 1861.24  5596.7 1862.95  5686.3 1865.86  5837.7 1868.70
#Mann=3,-1,0
  4730.3    0.05       0  4994.4    0.05       0  4999.3    0.05       0
Bank Sta=4994.4,4999.3
Exp/Cntr=0.3,0.1

Type RM Length L Ch R = 1,5899,486,486,486
BEGIN DESCRIPTION:
Deadman 46 12.0
END DESCRIPTION:
XS GIS Cut Line= 3
      1646705.00      6874387.99      1646655.00      6874838.00
      1646891.42      6875443.71
#Sta/Elev= 30
  4546.3 1867.58  4646.9 1864.85  4707.3 1862.07  4747.5 1859.62  4767.7 1859.65
  4787.8 1857.85  4807.9 1858.44  4818.0 1856.77  4858.2 1855.12  4888.4 1854.40
  4928.7 1854.37  4938.7 1853.59  4986.5 1851.94  4986.8 1851.44  4991.2 1851.44
  4991.6 1851.94  5038.5 1852.76  5043.9 1853.74  5074.2 1853.09  5085.0 1853.27
  5106.4 1854.71  5192.3 1857.12  5224.5 1857.64  5231.4 1857.36  5315.6 1859.12
  5331.9 1858.88  5369.9 1859.87  5394.4 1859.77  5568.1 1862.98  5649.3 1863.86
#Mann=3,-1,0
  4546.3    0.05       0  4986.5    0.05       0  4991.6    0.05       0
Bank Sta=4986.5,4991.6
Exp/Cntr=0.3,0.1

Type RM Length L Ch R = 1,5413,446,446,446
BEGIN DESCRIPTION:
Mapping XS deba9254
END DESCRIPTION:
XS GIS Cut Line= 3
      1646291.50      6874573.45      1646325.00      6875134.59
      1646386.32      6875563.79
#Sta/Elev= 30
  4434.0 1858.42  4468.6 1858.51  4488.6 1856.44  4528.7 1854.68  4575.2 1853.01
  4580.2 1853.21  4618.9 1852.26  4739.1 1851.35  4779.2 1851.62  4789.2 1852.14
  4859.3 1851.61  4949.5 1851.86  4969.5 1851.33  4979.5 1850.06  4992.7 1849.64
  4993.1 1849.14  4997.5 1849.14  4998.0 1849.64  5009.7 1851.03  5028.2 1852.37
  5033.2 1851.57  5060.2 1853.51  5070.3 1853.49  5098.9 1854.86  5103.9 1854.31
  5120.8 1855.35  5245.3 1857.00  5272.3 1857.89  5302.6 1858.04  5429.7 1860.80
#Mann=3,-1,0
  4434.0    0.05       0  4992.7    0.03       0  4998.0    0.05       0
Bank Sta=4992.7,4998
Exp/Cntr=0.3,0.1

Type RM Length L Ch R = 1,4967,443,443,443
BEGIN DESCRIPTION:
Deadman 46 11.0
END DESCRIPTION:
XS GIS Cut Line= 3
      1646030.00      6874513.01      1645955.00      6874938.00
      1646254.99      6875687.97
#Sta/Elev= 30
  4569.0 1859.42  4584.2 1858.64  4594.4 1858.76  4604.5 1857.78  4635.0 1858.24
  4665.5 1857.40  4682.4 1856.05  4687.5 1856.17  4767.0 1851.98  4949.8 1848.76
  4987.8 1846.84  4988.2 1846.34  4992.7 1846.34  4993.1 1846.84  5003.2 1847.03
  5010.0 1847.94  5015.4 1847.59  5063.8 1849.33  5069.2 1847.71  5086.7 1848.14
  5093.5 1849.09  5098.8 1847.44  5117.7 1848.32  5123.1 1847.78  5140.6 1850.44
  5147.3 1850.63  5152.7 1850.20  5183.7 1851.20  5333.1 1852.86  5808.3 1862.51
#Mann=3,-1,0
  4569.0    0.05       0  4987.8    0.05       0  4993.1    0.05       0
Bank Sta=4987.8,4993.1
Exp/Cntr=0.3,0.1

Type RM Length L Ch R = 1,4524,422,422,422
BEGIN DESCRIPTION:
Deadman 46 10.0
END DESCRIPTION:
XS GIS Cut Line= 3
      1645480.00      6874663.00      1645555.00      6874888.00
      1646104.98      6875637.98
#Sta/Elev= 30
  4757.0 1856.39  4793.9 1856.40  4846.6 1852.59  4888.8 1850.63  4930.9 1849.42
  4952.0 1847.55  4981.0 1844.16  4981.4 1843.66  4985.9 1843.66  4986.3 1844.16
  4997.3 1844.21  5022.4 1846.35  5066.3 1847.34  5101.8 1847.13  5137.3 1847.62
  5143.5 1847.25  5158.2 1848.22  5180.2 1847.48  5287.8 1847.88  5373.5 1850.33
  5488.5 1851.46  5494.7 1851.95  5524.0 1851.82  5588.8 1852.89  5745.5 1856.36
  5760.2 1856.61  5766.4 1856.27  5787.8 1857.31  5852.1 1859.11  5924.2 1860.58
#Mann=3,-1,0
  4757.0    0.05       0  4981.0    0.03       0  4986.3    0.05       0
Bank Sta=4981,4986.3
Exp/Cntr=0.3,0.1

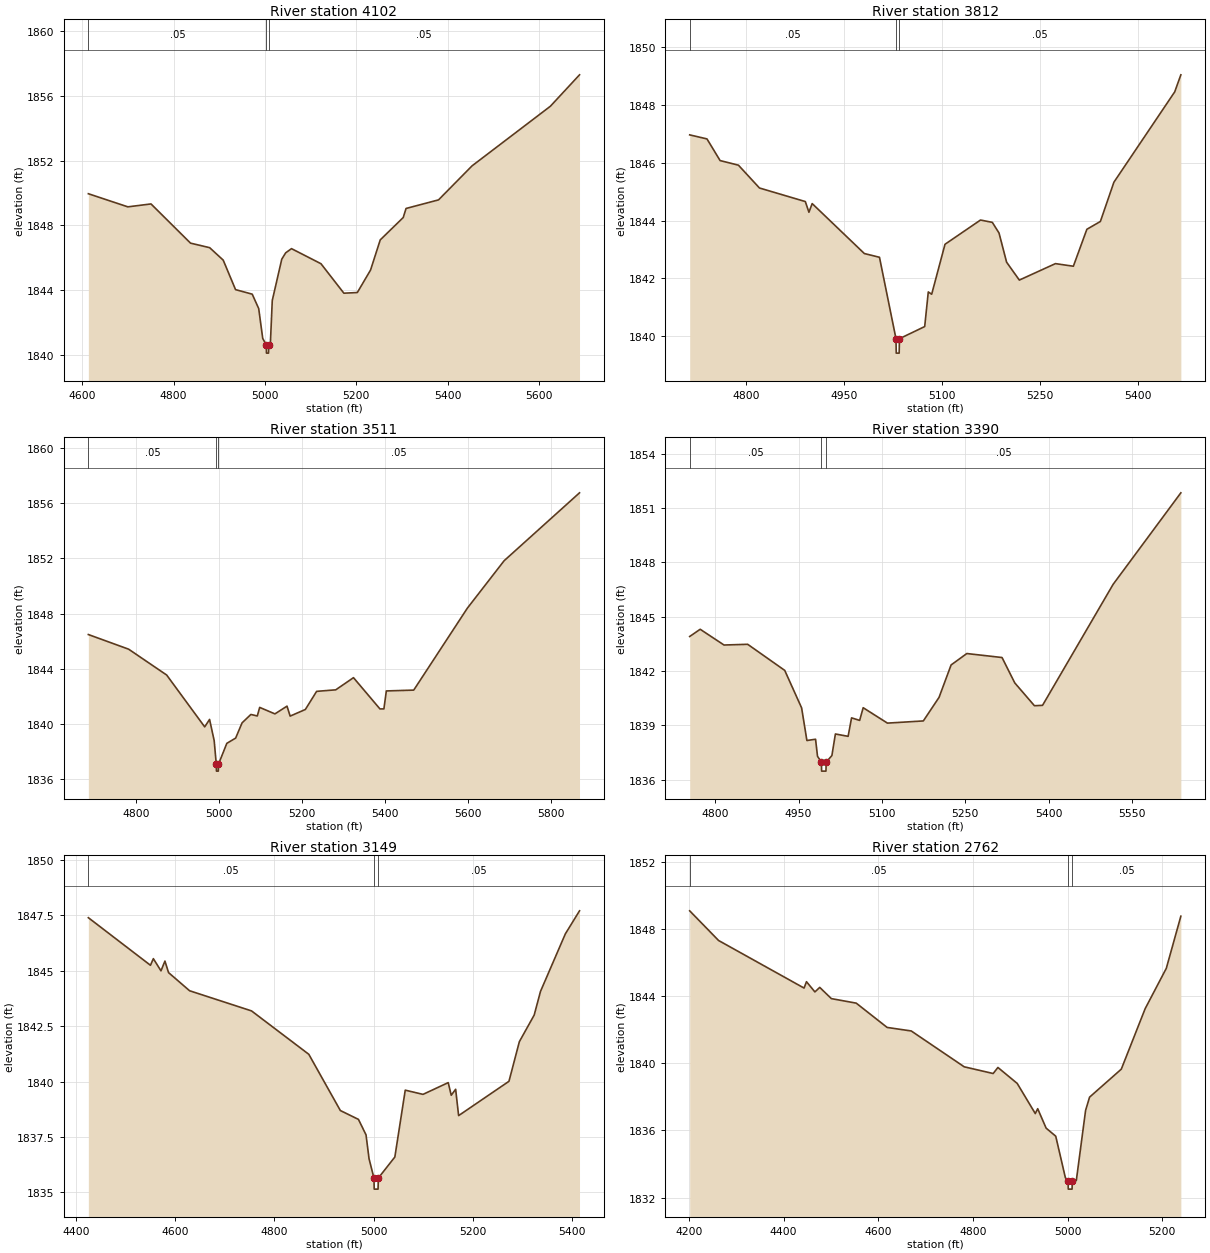
Type RM Length L Ch R = 1,4102,290,290,290
BEGIN DESCRIPTION:
Deadman 46 9.0
END DESCRIPTION:
XS GIS Cut Line= 3
      1645079.98      6874862.97      1645305.00      6875188.00
      1645705.00      6875738.01
#Sta/Elev= 30
  4613.4 1849.95  4699.9 1849.14  4750.6 1849.32  4837.1 1846.90  4879.0 1846.62
  4908.7 1845.85  4935.7 1844.03  4972.2 1843.75  4986.4 1842.86  4995.2 1841.02
  5003.0 1840.61  5003.4 1840.11  5007.9 1840.11  5008.3 1840.61  5011.8 1840.61
  5016.1 1843.36  5036.9 1845.91  5045.4 1846.30  5058.2 1846.56  5122.7 1845.63
  5172.9 1843.81  5202.3 1843.85  5231.3 1845.24  5252.5 1847.10  5302.8 1848.48
  5309.0 1849.04  5380.1 1849.57  5453.5 1851.67  5625.0 1855.35  5688.8 1857.29
#Mann=3,-1,0
  4613.4    0.05       0  5003.0    0.03       0  5008.3    0.05       0
Bank Sta=5003,5008.3
Exp/Cntr=0.3,0.1

Type RM Length L Ch R = 1,3812,301,301,301
BEGIN DESCRIPTION:
Mapping XS ac10f47a
END DESCRIPTION:
XS GIS Cut Line= 3
      1645022.64      6875011.61      1645050.01      6875299.01
      1645170.22      6875747.07
#Sta/Elev= 30
  4713.7 1846.97  4740.2 1846.83  4760.3 1846.08  4788.4 1845.92  4820.6 1845.13
  4890.9 1844.66  4896.4 1844.29  4901.4 1844.59  4981.3 1842.86  5004.5 1842.73
  5029.8 1839.91  5030.2 1839.41  5034.7 1839.41  5035.1 1839.91  5073.8 1840.33
  5079.3 1841.53  5084.5 1841.45  5104.9 1843.18  5159.3 1844.02  5177.4 1843.94
  5187.7 1843.57  5199.3 1842.56  5218.8 1841.94  5274.1 1842.51  5301.6 1842.42
  5322.3 1843.70  5343.0 1843.97  5363.7 1845.33  5456.9 1848.46  5466.3 1849.05
#Mann=3,-1,0
  4713.7    0.05       0  5029.8    0.05       0  5035.1    0.05       0
Bank Sta=5029.8,5035.1
Exp/Cntr=0.3,0.1

Type RM Length L Ch R = 1,3511,121,121,121
BEGIN DESCRIPTION:
Deadman 46 8.0
END DESCRIPTION:
XS GIS Cut Line= 3
      1644930.00      6874962.99      1644798.23      6875247.01
      1645255.02      6875988.04
#Sta/Elev= 30
  4685.9 1846.48  4783.0 1845.42  4874.7 1843.55  4966.3 1839.80  4978.0 1840.34
  4989.1 1838.81  4994.2 1837.10  4994.6 1836.60  4999.1 1836.60  4999.5 1837.10
  5019.6 1838.61  5040.9 1838.99  5056.3 1840.09  5077.6 1840.70  5093.0 1840.59
  5098.8 1841.21  5135.5 1840.74  5164.6 1841.30  5172.2 1840.58  5208.9 1841.06
  5236.0 1842.37  5282.1 1842.48  5324.8 1843.36  5388.6 1841.10  5398.1 1841.10
  5404.0 1842.40  5470.0 1842.46  5599.3 1848.39  5687.9 1851.82  5869.5 1856.73
#Mann=3,-1,0
  4685.9    0.05       0  4994.2    0.05       0  4999.5    0.05       0
Bank Sta=4994.2,4999.5
Exp/Cntr=0.3,0.1

Type RM Length L Ch R = 1,3390,241,241,241
BEGIN DESCRIPTION:
Mapping XS 1831600c
END DESCRIPTION:
XS GIS Cut Line= 3
      1644517.03      6875254.69      1644735.77      6875335.42
      1645126.39      6875856.25
#Sta/Elev= 30
  4754.0 1843.90  4772.9 1844.30  4815.8 1843.43  4858.4 1843.47  4925.1 1842.03
  4955.5 1839.96  4965.0 1838.16  4980.6 1838.23  4984.1 1837.29  4991.0 1836.97
  4991.5 1836.47  4999.3 1836.47  4999.8 1836.97  5010.0 1837.33  5016.3 1838.52
  5039.2 1838.39  5045.4 1839.41  5060.0 1839.27  5066.3 1839.97  5110.0 1839.12
  5174.6 1839.24  5202.9 1840.54  5224.6 1842.33  5252.9 1842.96  5316.3 1842.74
  5339.2 1841.34  5374.6 1840.08  5389.2 1840.10  5516.3 1846.78  5638.2 1851.83
#Mann=3,-1,0
  4754.0    0.05       0  4991.0    0.05       0  4999.8    0.05       0
Bank Sta=4991,4999.8
Exp/Cntr=0.3,0.1

Type RM Length L Ch R = 1,3149,387,387,387
BEGIN DESCRIPTION:
Deadman 46 7.0
END DESCRIPTION:
XS GIS Cut Line= 3
      1644373.54      6875076.72      1644681.71      6875571.53
      1645020.15      6875801.49
#Sta/Elev= 30
  4424.0 1847.40  4549.5 1845.25  4555.3 1845.55  4570.7 1845.00  4578.7 1845.44
  4586.0 1844.92  4628.5 1844.10  4753.6 1843.19  4869.3 1841.23  4933.0 1838.69
  4969.6 1838.29  4984.9 1837.59  4991.0 1836.51  5000.9 1835.64  5001.4 1835.14
  5009.2 1835.14  5009.7 1835.64  5043.1 1836.59  5064.1 1839.61  5100.0 1839.42
  5150.9 1839.95  5157.0 1839.38  5165.9 1839.65  5171.9 1838.46  5273.6 1840.01
  5294.6 1841.80  5324.5 1843.00  5337.3 1844.07  5387.5 1846.67  5416.1 1847.71
#Mann=3,-1,0
  4424.0    0.05       0  5000.9    0.05       0  5009.7    0.05       0
Bank Sta=5000.9,5009.7
Exp/Cntr=0.3,0.1

Type RM Length L Ch R = 1,2762,462,462,462
BEGIN DESCRIPTION:
Deadman 46 6.0
END DESCRIPTION:
XS GIS Cut Line= 3
      1644255.00      6875038.02      1644405.00      6875838.00
      1644504.99      6876037.97
#Sta/Elev= 30
  4201.8 1849.11  4262.8 1847.34  4443.4 1844.50  4448.5 1844.88  4466.3 1844.27
  4476.5 1844.54  4501.1 1843.87  4553.6 1843.60  4618.9 1842.15  4669.8 1841.94
  4781.7 1839.80  4842.8 1839.40  4852.9 1839.76  4893.6 1838.81  4931.8 1837.01
  4936.9 1837.30  4954.7 1836.14  4975.0 1835.66  4995.4 1833.18  5001.0 1833.00
  5001.5 1832.50  5009.5 1832.50  5010.0 1833.00  5018.5 1833.02  5038.1 1837.20
  5046.5 1837.99  5113.5 1839.66  5163.9 1843.27  5208.6 1845.68  5239.3 1848.79
#Mann=3,-1,0
  4201.8    0.05       0  5001.0    0.03       0  5010.0    0.05       0
Bank Sta=5001,5010
Exp/Cntr=0.3,0.1