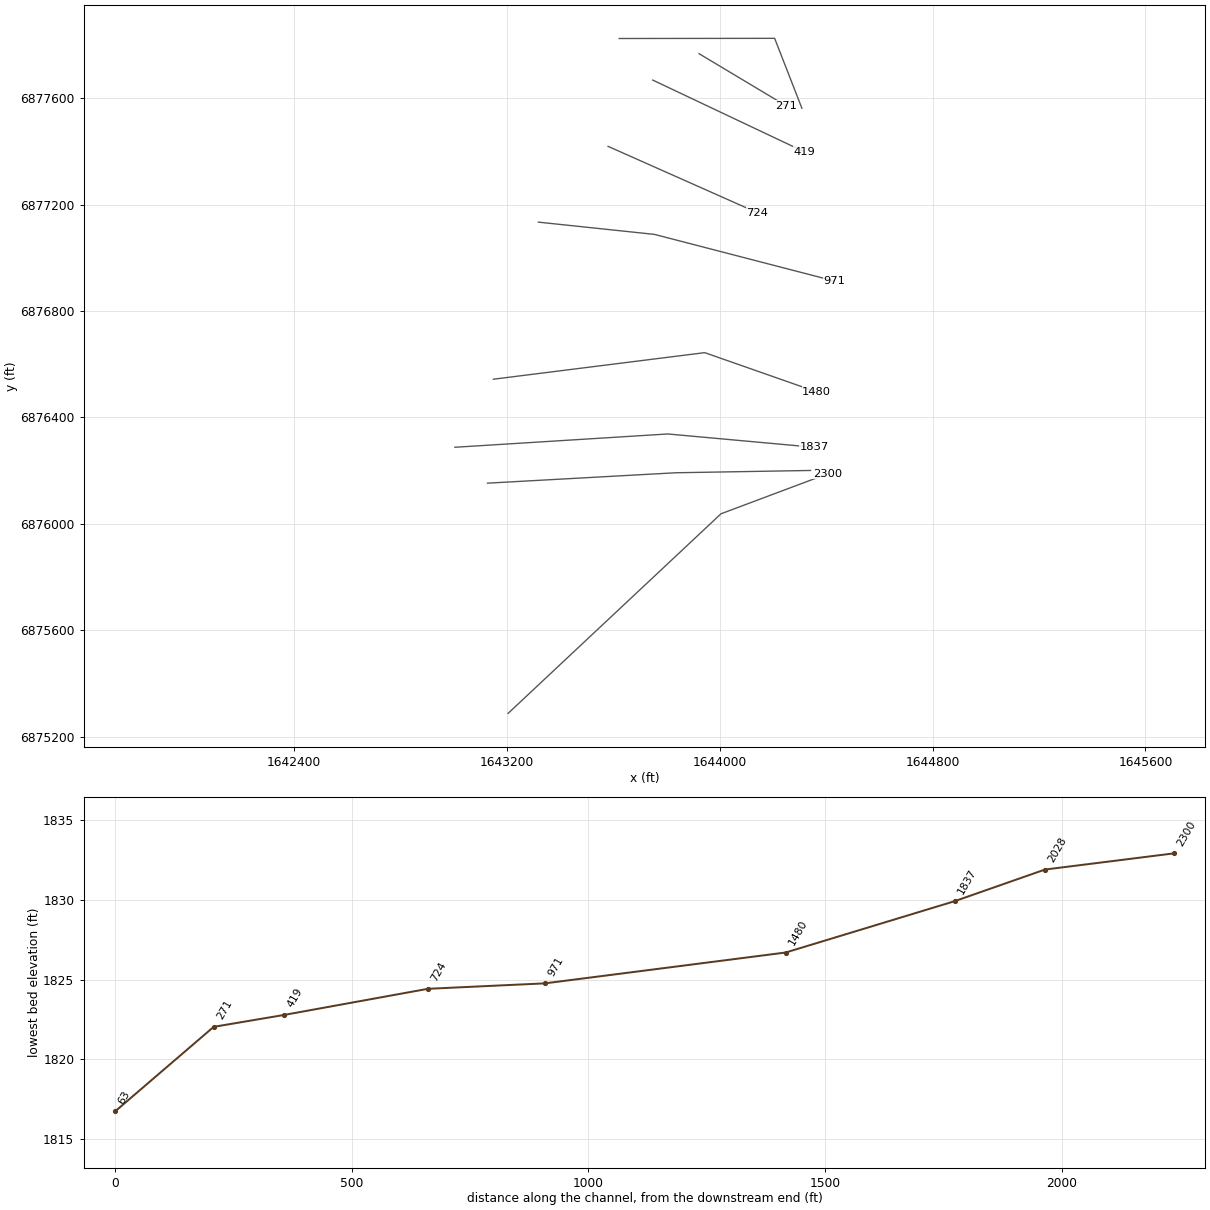
HEC-RAS study Deadman 46.prj: Deadman 46 Base Level Engineering

--- Deadman 46.g01 (geometry) --- (continued)

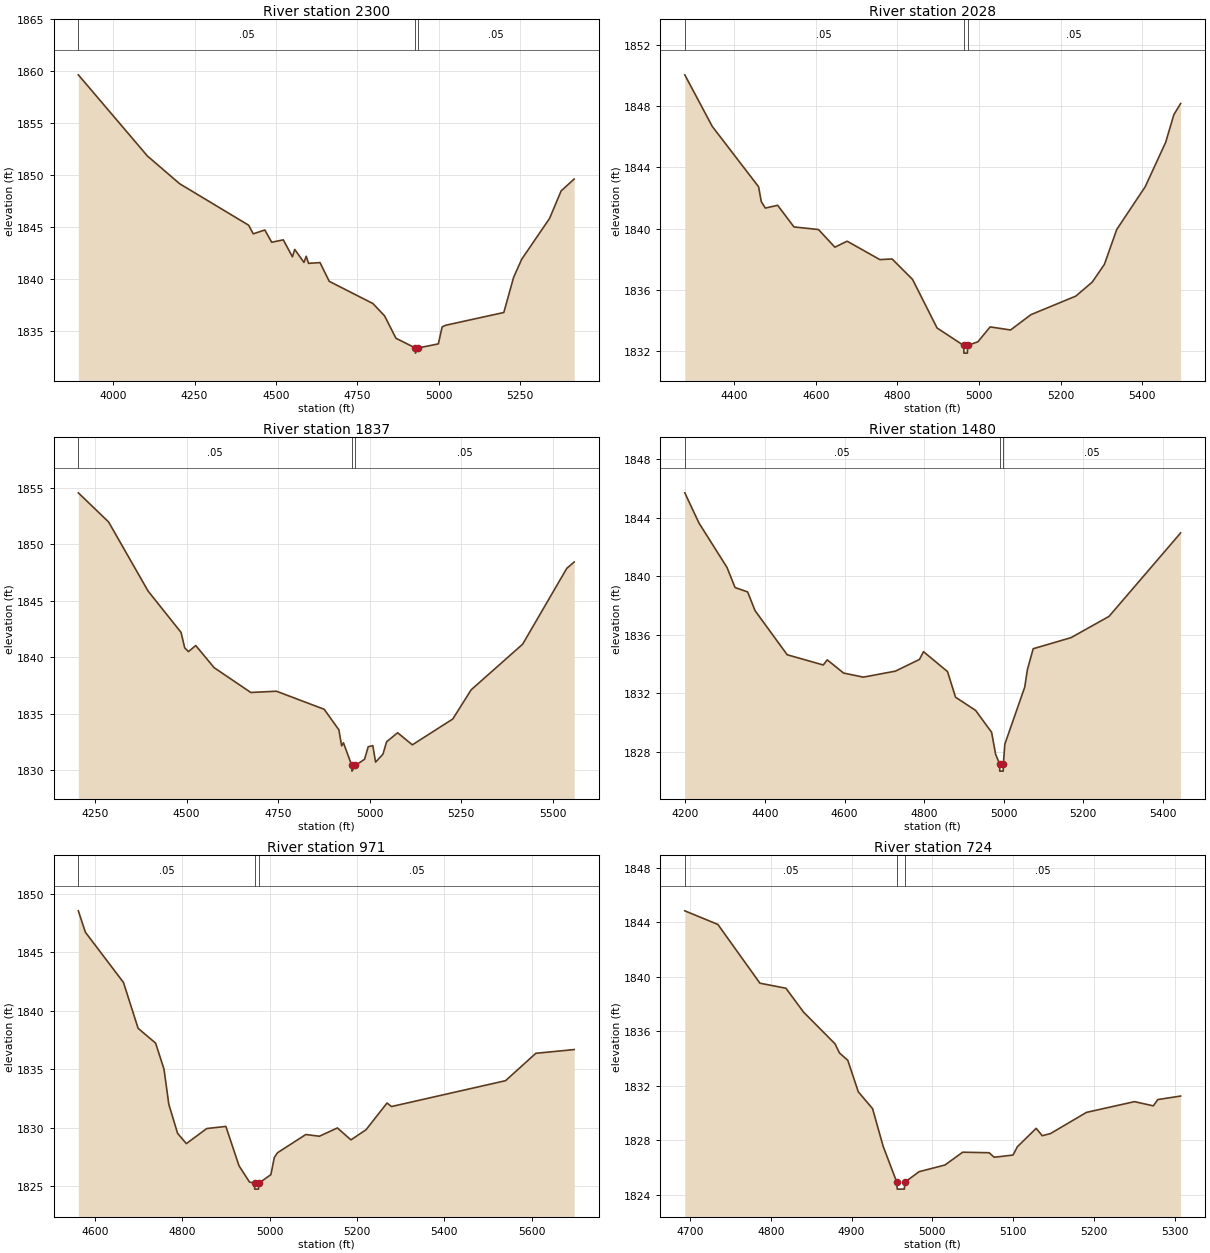
Type RM Length L Ch R = 1,2300,272,272,272
BEGIN DESCRIPTION:
Deadman 46 5.0
END DESCRIPTION:
XS GIS Cut Line= 3
      1643204.96      6875287.97      1644005.00      6876038.00
      1644404.97      6876187.99
#Sta/Elev= 30
  3892.9 1859.67  4105.2 1851.86  4204.3 1849.19  4416.3 1845.20  4430.5 1844.37
  4466.1 1844.74  4487.2 1843.56  4522.8 1843.79  4550.9 1842.16  4558.0 1842.87
  4586.3 1841.62  4593.2 1842.21  4600.5 1841.53  4635.7 1841.60  4664.0 1839.80
  4798.3 1837.66  4834.0 1836.48  4869.1 1834.32  4928.4 1833.39  4928.9 1832.89
  4937.9 1833.39  4999.3 1833.78  5010.9 1835.41  5021.6 1835.57  5200.5 1836.80
  5230.7 1840.19  5255.6 1841.93  5341.1 1845.85  5376.7 1848.50  5416.7 1849.64
#Mann=3,-1,0
  3892.9    0.05       0  4928.4    0.05       0  4937.9    0.05       0
Bank Sta=4928.4,4937.9
Exp/Cntr=0.3,0.1

Type RM Length L Ch R = 1,2028,191,191,191
BEGIN DESCRIPTION:
Mapping XS a59cdf49
END DESCRIPTION:
XS GIS Cut Line= 3
      1643127.88      6876153.13      1643835.36      6876192.19
      1644341.62      6876200.84
#Sta/Elev= 30
  4279.0 1850.03  4346.2 1846.67  4459.8 1842.73  4466.4 1841.76  4476.4 1841.34
  4506.5 1841.52  4546.5 1840.11  4606.6 1839.94  4646.7 1838.79  4676.7 1839.18
  4756.9 1837.98  4786.9 1838.02  4837.0 1836.69  4897.1 1833.52  4962.4 1832.38
  4962.9 1831.88  4971.4 1831.88  4971.9 1832.38  4997.2 1832.62  5027.2 1833.59
  5077.2 1833.39  5127.2 1834.39  5237.2 1835.60  5277.2 1836.51  5307.2 1837.67
  5337.3 1839.94  5407.3 1842.74  5457.3 1845.63  5477.3 1847.43  5493.9 1848.16
#Mann=3,-1,0
  4279.0    0.05       0  4962.4    0.05       0  4971.9    0.05       0
Bank Sta=4962.4,4971.9
Exp/Cntr=0.3,0.1

Type RM Length L Ch R = 1,1837,357,357,357
BEGIN DESCRIPTION:
Deadman 46 4.0
END DESCRIPTION:
XS GIS Cut Line= 3
      1643005.02      6876288.00      1643805.00      6876338.00
      1644354.99      6876288.00
#Sta/Elev= 30
  4204.6 1854.56  4287.2 1851.98  4395.0 1845.86  4485.1 1842.19  4495.1 1840.82
  4505.2 1840.49  4525.2 1841.03  4575.3 1839.07  4675.5 1836.87  4745.6 1836.98
  4875.9 1835.38  4916.0 1833.56  4923.5 1832.14  4928.5 1832.41  4951.2 1830.40
  4951.7 1829.90  4960.8 1830.40  4986.1 1830.95  4996.1 1832.06  5008.7 1832.16
  5016.2 1830.70  5036.3 1831.40  5046.3 1832.50  5076.4 1833.30  5116.6 1832.23
  5227.0 1834.52  5277.3 1837.11  5417.8 1841.15  5538.3 1847.87  5558.4 1848.43
#Mann=3,-1,0
  4204.6    0.05       0  4951.2    0.05       0  4960.8    0.05       0
Bank Sta=4951.2,4960.8
Exp/Cntr=0.3,0.1

Type RM Length L Ch R = 1,1480,509,509,509
BEGIN DESCRIPTION:
Deadman 46 3.0
END DESCRIPTION:
XS GIS Cut Line= 3
      1643149.63      6876543.76      1643943.86      6876643.58
      1644364.87      6876496.01
#Sta/Elev= 30
  4198.4 1845.70  4234.0 1843.64  4304.6 1840.60  4324.8 1839.23  4356.4 1838.93
  4375.1 1837.65  4455.8 1834.64  4546.5 1833.94  4556.6 1834.29  4597.6 1833.39
  4647.3 1833.11  4727.9 1833.52  4788.4 1834.32  4798.5 1834.85  4858.9 1833.49
  4879.1 1831.74  4929.5 1830.84  4969.8 1829.34  4979.9 1827.84  4989.8 1827.19
  4990.3 1826.69  4998.9 1826.69  4999.4 1827.19  5003.0 1828.53  5053.1 1832.43
  5059.7 1833.61  5074.3 1835.05  5169.6 1835.81  5265.0 1837.26  5445.0 1842.96
#Mann=3,-1,0
  4198.4    0.05       0  4989.8    0.05       0  4999.4    0.05       0
Bank Sta=4989.8,4999.4
Exp/Cntr=0.3,0.1

Type RM Length L Ch R = 1,971,247,247,247
BEGIN DESCRIPTION:
Deadman 46 2.0
END DESCRIPTION:
XS GIS Cut Line= 3
      1643318.85      6877134.03      1643755.00      6877088.00
      1644430.01      6876913.00
#Sta/Elev= 30
  4561.6 1848.55  4577.8 1846.72  4665.0 1842.43  4698.5 1838.51  4738.7 1837.24
  4757.9 1835.01  4768.9 1832.01  4789.0 1829.53  4809.1 1828.65  4855.8 1829.94
  4899.6 1830.12  4929.8 1826.75  4953.7 1825.37  4965.2 1825.26  4965.7 1824.76
  4974.3 1824.76  4974.8 1825.26  5002.8 1826.00  5010.5 1827.46  5017.9 1827.87
  5082.8 1829.43  5113.8 1829.28  5155.1 1829.99  5186.1 1828.97  5220.8 1829.84
  5268.8 1832.12  5279.1 1831.82  5540.3 1834.03  5609.7 1836.37  5697.5 1836.69
#Mann=3,-1,0
  4561.6    0.05       0  4965.2    0.03       0  4974.8    0.05       0
Bank Sta=4965.2,4974.8
Exp/Cntr=0.3,0.1

Type RM Length L Ch R = 1,724,305,305,305
BEGIN DESCRIPTION:
Mapping XS 78c83f51
END DESCRIPTION:
XS GIS Cut Line= 2
      1643580.63      6877418.84      1644141.53      6877169.55
#Sta/Elev= 30
  4693.6 1844.84  4734.6 1843.84  4786.6 1839.53  4818.8 1839.16  4840.6 1837.41
  4879.6 1835.08  4885.1 1834.41  4895.4 1833.87  4908.4 1831.56  4926.1 1830.32
  4939.1 1827.57  4956.1 1824.92  4956.6 1824.42  4965.4 1824.42  4965.9 1824.92
  4983.6 1825.70  5015.7 1826.19  5037.6 1827.13  5070.4 1827.09  5076.6 1826.76
  5099.9 1826.92  5105.3 1827.53  5128.6 1828.88  5136.1 1828.34  5146.4 1828.50
  5190.8 1830.05  5250.3 1830.84  5273.6 1830.53  5279.1 1830.99  5307.4 1831.25
#Mann=3,-1,0
  4693.6    0.05       0  4956.1    0.05       0  4965.9    0.05       0
Bank Sta=4956.1,4965.9
Exp/Cntr=0.3,0.1

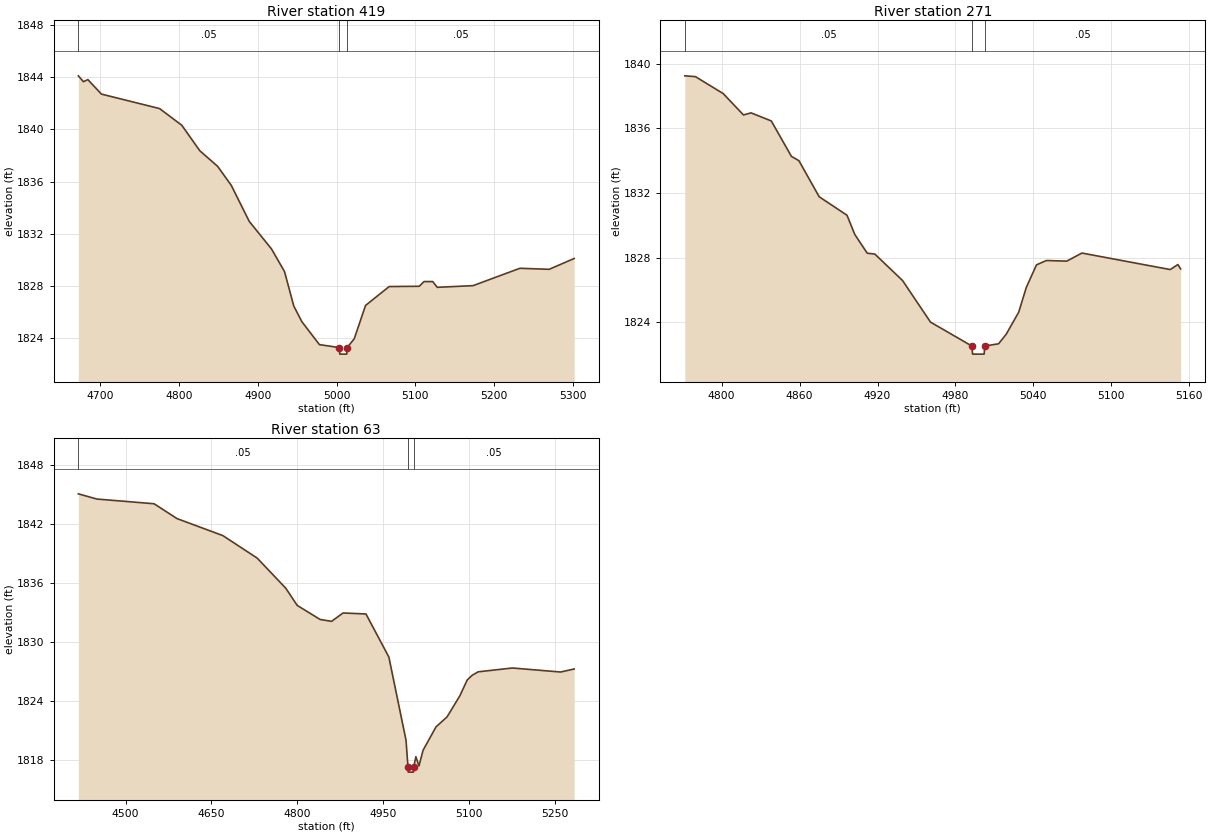
Type RM Length L Ch R = 1,419,148,148,148
BEGIN DESCRIPTION:
Mapping XS 8a07436e
END DESCRIPTION:
XS GIS Cut Line= 2
      1643748.54      6877667.89      1644317.17      6877398.77
#Sta/Elev= 30
  4672.3 1844.11  4678.8 1843.66  4684.4 1843.82  4701.6 1842.71  4775.4 1841.60
  4803.6 1840.32  4826.4 1838.37  4849.1 1837.17  4866.4 1835.71  4889.1 1832.96
  4917.4 1830.84  4933.9 1829.11  4945.7 1826.46  4956.0 1825.26  4978.2 1823.51
  5003.5 1823.28  5004.0 1822.78  5012.9 1822.78  5013.4 1823.28  5022.4 1823.96
  5036.7 1826.51  5066.7 1827.96  5104.9 1827.98  5110.9 1828.34  5122.0 1828.34
  5127.7 1827.90  5173.2 1828.03  5232.6 1829.36  5269.7 1829.28  5301.4 1830.11
#Mann=3,-1,0
  4672.3    0.05       0  5003.5    0.05       0  5013.4    0.05       0
Bank Sta=5003.5,5013.4
Exp/Cntr=0.3,0.1

Type RM Length L Ch R = 1,271,208,208,208
BEGIN DESCRIPTION:
Mapping XS df77ce6b
END DESCRIPTION:
XS GIS Cut Line= 2
      1643922.66      6877767.05      1644250.26      6877570.95
#Sta/Elev= 30
  4771.6 1839.25  4779.8 1839.20  4801.2 1838.15  4816.8 1836.83  4822.6 1836.96
  4838.2 1836.46  4853.7 1834.27  4859.5 1834.00  4875.1 1831.77  4896.5 1830.63
  4902.5 1829.44  4912.1 1828.28  4917.9 1828.23  4939.3 1826.59  4960.8 1824.02
  4992.7 1822.54  4993.2 1822.04  5002.1 1822.04  5002.6 1822.54  5013.2 1822.68
  5019.1 1823.27  5028.7 1824.63  5034.6 1826.17  5042.4 1827.56  5050.1 1827.83
  5065.7 1827.79  5077.4 1828.29  5145.4 1827.27  5151.3 1827.58  5153.4 1827.31
#Mann=3,-1,0
  4771.6    0.05       0  4992.7    0.05       0  5002.6    0.05       0
Bank Sta=4992.7,5002.6
Exp/Cntr=0.3,0.1

Type RM Length L Ch R = 1,63,0,0,0
BEGIN DESCRIPTION:
Deadman 46 1.0
END DESCRIPTION:
XS GIS Cut Line= 3
      1643622.69      6877824.13      1644206.66      6877824.76
      1644309.07      6877562.09
#Sta/Elev= 30
  4417.5 1845.09  4449.8 1844.56  4549.8 1844.08  4589.8 1842.57  4669.8 1840.84
  4729.8 1838.55  4779.8 1835.48  4799.8 1833.73  4839.8 1832.30  4859.8 1832.11
  4879.8 1832.96  4919.8 1832.86  4959.8 1828.48  4989.8 1820.00  4993.2 1817.26
  4993.7 1816.76  5002.6 1816.76  5003.1 1817.26  5007.0 1818.33  5012.4 1817.39
  5019.5 1818.98  5042.2 1821.37  5061.4 1822.38  5083.9 1824.54  5096.6 1826.14
  5105.3 1826.62  5115.7 1826.97  5175.5 1827.36  5259.7 1826.95  5283.4 1827.26
#Mann=3,-1,0
  4417.5    0.05       0  4993.2    0.05       0  5003.1    0.05       0
Bank Sta=4993.2,5003.1
Exp/Cntr=0.3,0.1

Chan Stop Cuts=-1