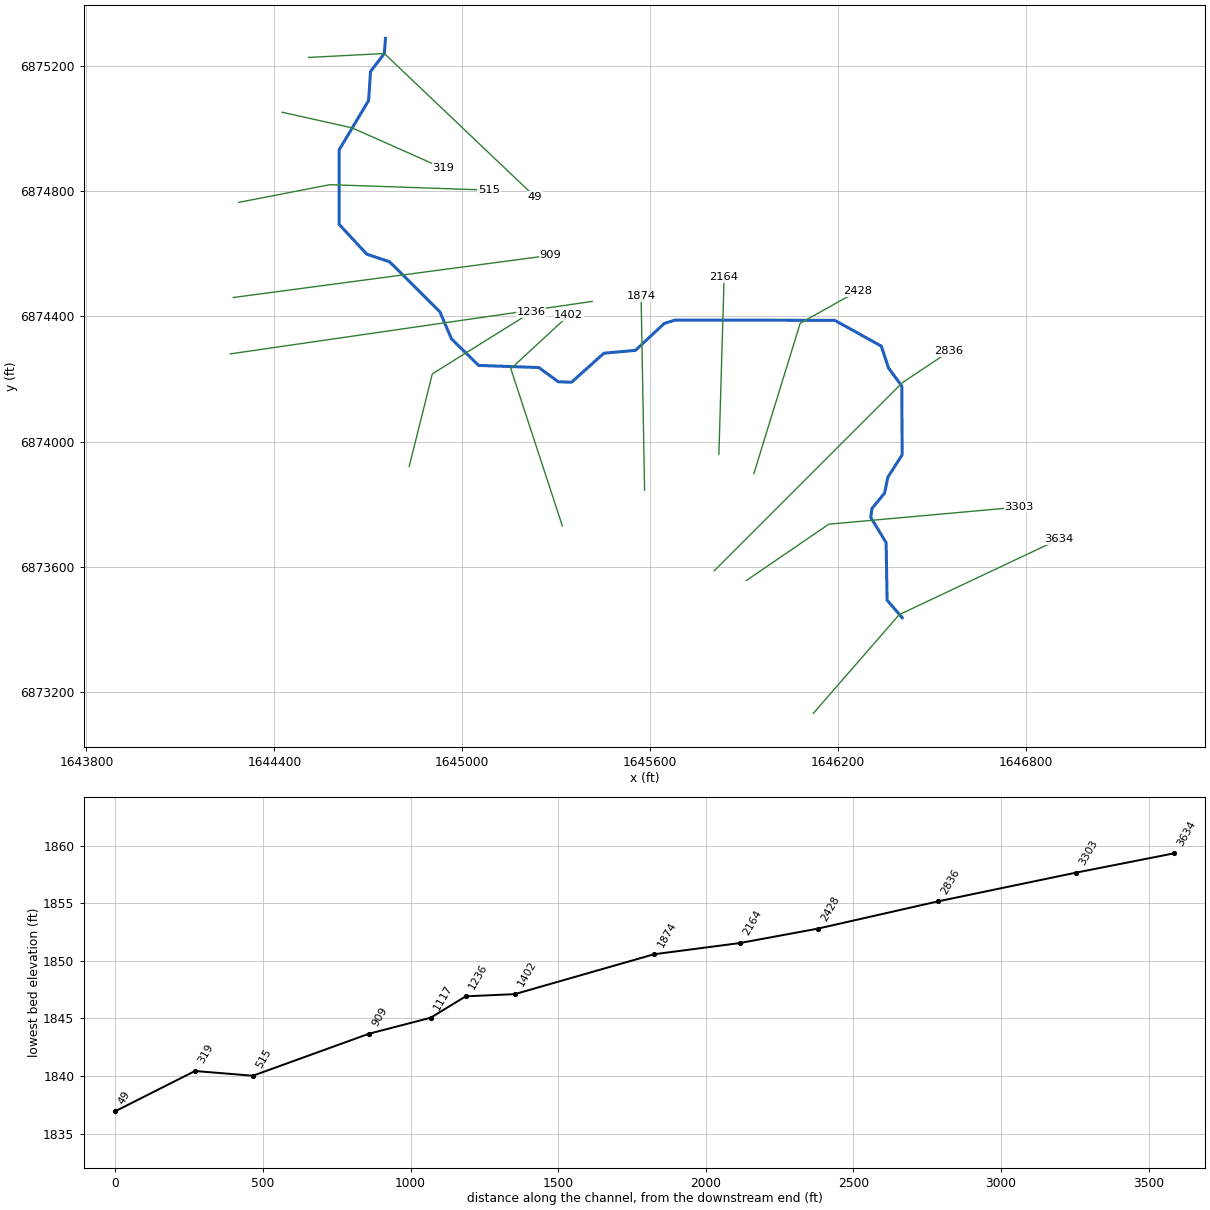
--- Deadman 47.prj (project) ---

Proj Title=Deadman 47 Base Level Engineering
Current Plan=p01
Default Exp/Contr=0.3,0.1
English Units
Geom File=g01
Flow File=f01
Plan File=p01
BEGIN DESCRIPTION:
Deadman 47
END DESCRIPTION:

--- Deadman 47.p01 (plan) ---

Plan Title=Multiple Run
Short Identifier=Multiple
Geom File=g01
Flow File=f01
Subcritical Flow
K Sum by GR= 0
Std Step Tol= 0.01
Critical Tol= 0.01
Num of Std Step Trials= 20
Max Error Tol= 0.3
Flow Tol Ratio= 0.001
Split Flow NTrial= 30
Split Flow Tol= 0.02
Split Flow Ratio= 0.02
Log Output Level= 0
Friction Slope Method= 1
Unsteady Friction Slope Method= 2
Unsteady Bridges Friction Slope Method= 1
Parabolic Critical Depth
Global Vel Dist=  1 , 1 , 1
Global Log Level= 0
CheckData=True
Encroach Param= -1, 0, 0, 0
BEGIN DESCRIPTION:
Multiple Run
END DESCRIPTION:

--- Deadman 47.f01 (steady flow) ---

Flow Title=Multiple
Number of Profiles=7
Profile Names=10-year,25-year,50-year,1pct_min,100-year,1pct_plu,500-year
River Rch & RM= Deadman 47,Reach-1,3634
     186     251     303     183     364     727     532
River Rch & RM= Deadman 47,Reach-1,3303
     277     383     471     288     574    1145     864
Boundary for River Rch & Prof#=Deadman 47,Reach-1,1
Up Type=0
Dn Type=3
Dn Slope=0.005
Boundary for River Rch & Prof#=Deadman 47,Reach-1,2
Up Type=0
Dn Type=3
Dn Slope=0.005
Boundary for River Rch & Prof#=Deadman 47,Reach-1,3
Up Type=0
Dn Type=3
Dn Slope=0.005
Boundary for River Rch & Prof#=Deadman 47,Reach-1,4
Up Type=0
Dn Type=3
Dn Slope=0.005
Boundary for River Rch & Prof#=Deadman 47,Reach-1,5
Up Type=0
Dn Type=3
Dn Slope=0.005
Boundary for River Rch & Prof#=Deadman 47,Reach-1,6
Up Type=0
Dn Type=3
Dn Slope=0.005
Boundary for River Rch & Prof#=Deadman 47,Reach-1,7
Up Type=0
Dn Type=3
Dn Slope=0.005

--- Deadman 47.g01 (geometry) ---

Geom Title=Existing Conditions

River Reach=Deadman 47,Reach-1
Reach XY= 30
      1646405.00      6873438.00      1646356.89      6873493.78
      1646353.76      6873677.50      1646304.71      6873758.18
      1646308.34      6873786.28      1646348.85      6873835.80
      1646359.19      6873886.26      1646404.94      6873958.03
      1646403.80      6874177.50      1646361.15      6874235.85
      1646338.52      6874305.06      1646189.79      6874387.49
      1645679.88      6874388.29      1645645.21      6874377.50
      1645553.50      6874291.63      1645452.58      6874282.46
      1645348.96      6874189.63      1645306.75      6874191.34
      1645244.50      6874236.76      1645052.53      6874243.45
      1644965.77      6874328.30      1644928.70      6874414.82
      1644768.21      6874574.37      1644695.30      6874598.77
      1644607.05      6874693.84      1644607.24      6874932.07
      1644701.18      6875089.58      1644707.23      6875182.08
      1644751.36      6875239.51      1644755.00      6875288.00

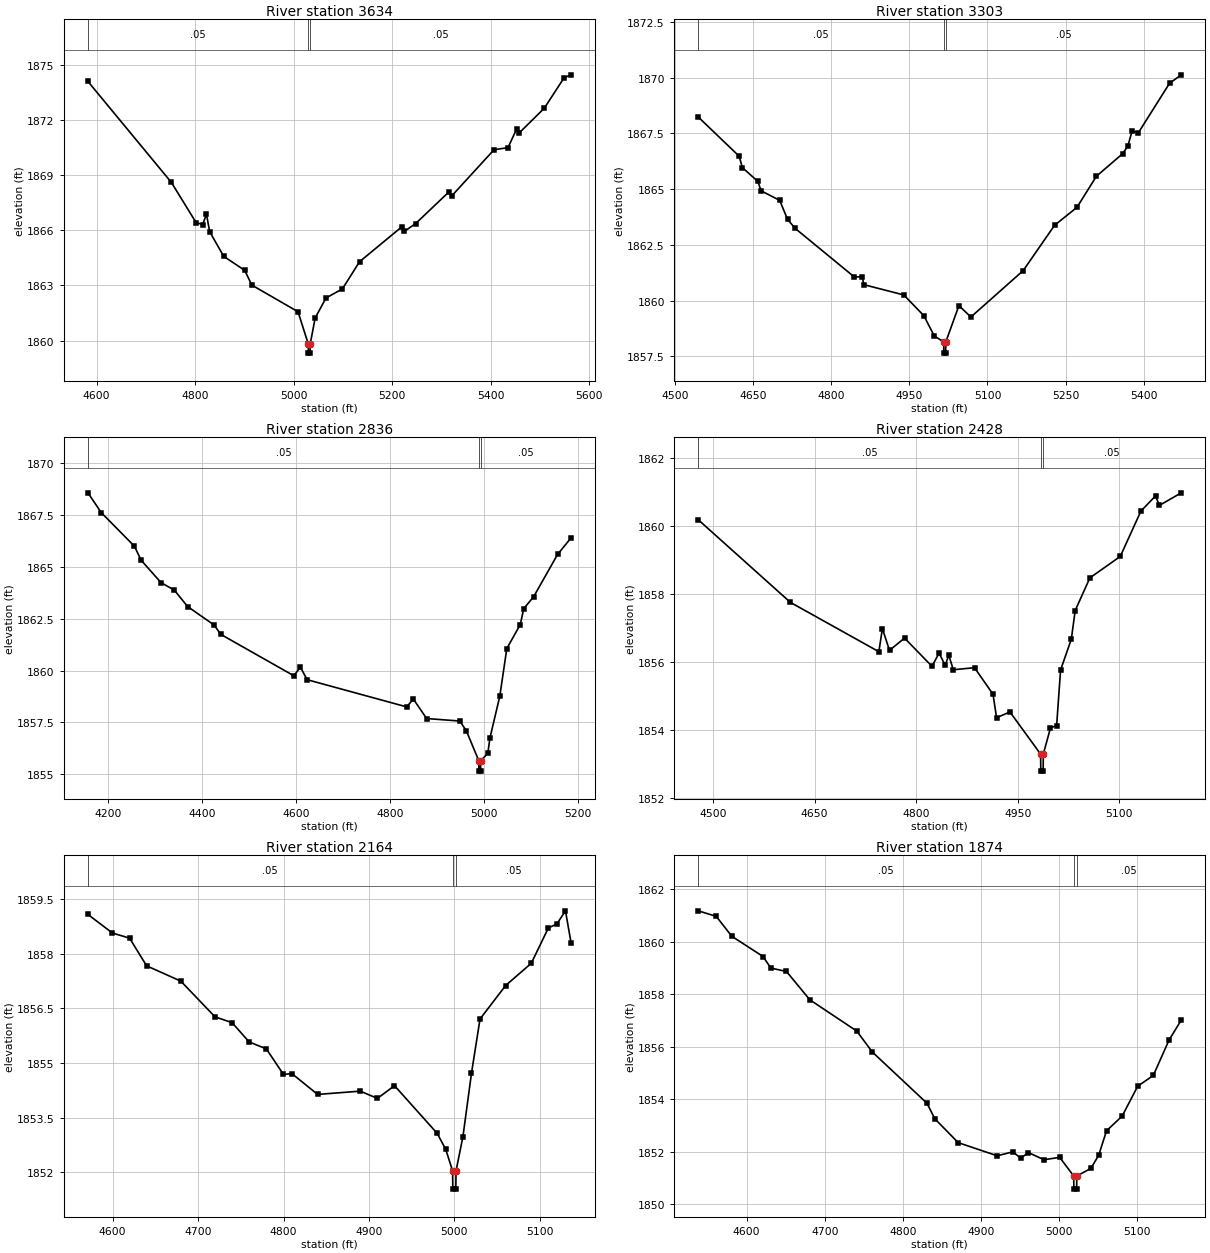
Type RM Length L Ch R = 1,3634,331,331,331
BEGIN DESCRIPTION:
Deadman 47 3.0
END DESCRIPTION:
XS GIS Cut Line= 3
      1646121.22      6873132.33      1646395.39      6873447.46
      1646904.97      6873687.99
#Sta/Elev= 30
  4582.3 1874.09  4751.8 1868.60  4801.9 1866.42  4815.4 1866.31  4823.0 1866.88
  4829.6 1865.92  4858.1 1864.58  4900.8 1863.82  4915.1 1863.02  5009.0 1861.57
  5029.8 1859.82  5030.1 1859.32  5033.6 1859.32  5033.8 1859.82  5043.8 1861.23
  5065.9 1862.32  5099.1 1862.81  5134.0 1864.29  5219.5 1866.18  5225.0 1865.94
  5247.8 1866.36  5316.1 1868.10  5321.7 1867.88  5407.2 1870.38  5435.5 1870.49
  5452.8 1871.49  5458.3 1871.29  5509.4 1872.64  5549.4 1874.29  5563.5 1874.45
#Mann=3,-1,0
  4582.3    0.05       0  5029.8    0.03       0  5033.8    0.05       0
Bank Sta=5029.8,5033.8
Exp/Cntr=0.3,0.1

Type RM Length L Ch R = 1,3303,467,467,467
BEGIN DESCRIPTION:
Mapping XS dfefea74
END DESCRIPTION:
XS GIS Cut Line= 3
      1645907.66      6873556.79      1646170.67      6873736.46
      1646777.39      6873791.15
#Sta/Elev= 30
  4544.5 1868.24  4623.2 1866.48  4629.3 1865.97  4659.1 1865.35  4665.2 1864.93
  4701.1 1864.50  4716.0 1863.65  4730.9 1863.24  4844.6 1861.06  4859.5 1861.08
  4862.6 1860.72  4939.3 1860.26  4977.8 1859.33  4997.9 1858.42  5016.0 1858.15
  5016.2 1857.65  5019.7 1857.65  5020.0 1858.15  5045.2 1859.78  5068.2 1859.27
  5168.6 1861.35  5228.8 1863.38  5272.0 1864.19  5309.2 1865.58  5359.4 1866.59
  5369.4 1866.92  5377.9 1867.62  5389.5 1867.52  5449.7 1869.75  5472.2 1870.13
#Mann=3,-1,0
  4544.5    0.05       0  5016.0    0.03       0  5020.0    0.05       0
Bank Sta=5016,5020
Exp/Cntr=0.3,0.1

Type RM Length L Ch R = 1,2836,408,408,408
BEGIN DESCRIPTION:
Deadman 47 2.0
END DESCRIPTION:
XS GIS Cut Line= 3
      1645804.98      6873587.98      1646405.00      6874188.00
      1646554.97      6874287.98
#Sta/Elev= 30
  4157.0 1868.55  4185.3 1867.60  4256.0 1865.98  4270.2 1865.31  4312.6 1864.23
  4340.9 1863.87  4369.2 1863.08  4425.7 1862.19  4439.9 1861.74  4595.4 1859.75
  4609.6 1860.16  4623.7 1859.56  4835.9 1858.25  4850.0 1858.63  4878.3 1857.69
  4949.0 1857.57  4963.1 1857.09  4989.4 1855.66  4989.7 1855.16  4993.2 1855.16
  4993.4 1855.66  5008.6 1856.01  5013.1 1856.75  5034.1 1858.76  5049.1 1861.06
  5077.7 1862.21  5085.2 1862.98  5106.2 1863.55  5157.3 1865.59  5185.8 1866.38
#Mann=3,-1,0
  4157.0    0.05       0  4989.4    0.05       0  4993.4    0.05       0
Bank Sta=4989.4,4993.4
Exp/Cntr=0.3,0.1

Type RM Length L Ch R = 1,2428,264,264,264
BEGIN DESCRIPTION:
Mapping XS 65217714
END DESCRIPTION:
XS GIS Cut Line= 3
      1645931.40      6873897.93      1646079.34      6874378.05
      1646263.57      6874481.33
#Sta/Elev= 30
  4478.0 1860.18  4614.2 1857.75  4744.9 1856.30  4750.1 1856.98  4760.6 1856.34
  4782.8 1856.70  4823.4 1855.87  4833.8 1856.26  4842.9 1855.90  4848.2 1856.20
  4854.8 1855.77  4886.2 1855.83  4913.5 1855.05  4918.8 1854.36  4938.5 1854.53
  4983.8 1853.29  4984.1 1852.79  4987.6 1852.79  4987.8 1853.29  4998.4 1854.06
  5007.5 1854.13  5013.3 1855.76  5029.2 1856.67  5034.9 1857.51  5056.6 1858.47
  5101.5 1859.10  5131.9 1860.43  5153.6 1860.88  5159.3 1860.60  5191.6 1860.97
#Mann=3,-1,0
  4478.0    0.05       0  4983.8    0.05       0  4987.8    0.05       0
Bank Sta=4983.8,4987.8
Exp/Cntr=0.3,0.1

Type RM Length L Ch R = 1,2164,290,290,290
BEGIN DESCRIPTION:
Mapping XS 2e13f595
END DESCRIPTION:
XS GIS Cut Line= 2
      1645819.72      6873959.34      1645836.42      6874524.49
#Sta/Elev= 30
  4571.1 1859.08  4599.8 1858.57  4619.8 1858.43  4639.8 1857.67  4679.8 1857.25
  4719.8 1856.27  4739.8 1856.11  4759.8 1855.58  4779.9 1855.39  4799.9 1854.69
  4809.9 1854.71  4839.9 1854.14  4889.9 1854.23  4909.9 1854.03  4929.9 1854.38
  4979.9 1853.07  4989.9 1852.63  4997.9 1852.04  4998.2 1851.54  5001.7 1851.54
  5001.9 1852.04  5010.0 1852.98  5020.0 1854.72  5030.0 1856.21  5060.0 1857.13
  5090.0 1857.74  5110.0 1858.71  5120.0 1858.82  5130.0 1859.18  5136.5 1858.31
#Mann=3,-1,0
  4571.1    0.05       0  4997.9    0.05       0  5001.9    0.05       0
Bank Sta=4997.9,5001.9
Exp/Cntr=0.3,0.1

Type RM Length L Ch R = 1,1874,472,472,472
BEGIN DESCRIPTION:
Mapping XS 268d9459
END DESCRIPTION:
XS GIS Cut Line= 2
      1645582.43      6873844.88      1645571.28      6874463.78
#Sta/Elev= 30
  4537.9 1861.17  4561.0 1860.96  4581.0 1860.20  4621.0 1859.43  4631.0 1858.99
  4651.0 1858.86  4681.0 1857.78  4741.1 1856.59  4761.1 1855.79  4831.1 1853.84
  4841.1 1853.25  4871.1 1852.34  4921.1 1851.84  4941.1 1851.99  4951.1 1851.75
  4961.1 1851.96  4981.1 1851.69  5001.1 1851.78  5019.1 1851.07  5019.3 1850.57
  5022.8 1850.57  5023.1 1851.07  5041.1 1851.36  5051.1 1851.86  5061.1 1852.79
  5081.1 1853.35  5101.1 1854.49  5121.1 1854.90  5141.1 1856.24  5156.9 1857.01
#Mann=3,-1,0
  4537.9    0.05       0  5019.1    0.03       0  5023.1    0.05       0
Bank Sta=5019.1,5023.1
Exp/Cntr=0.3,0.1

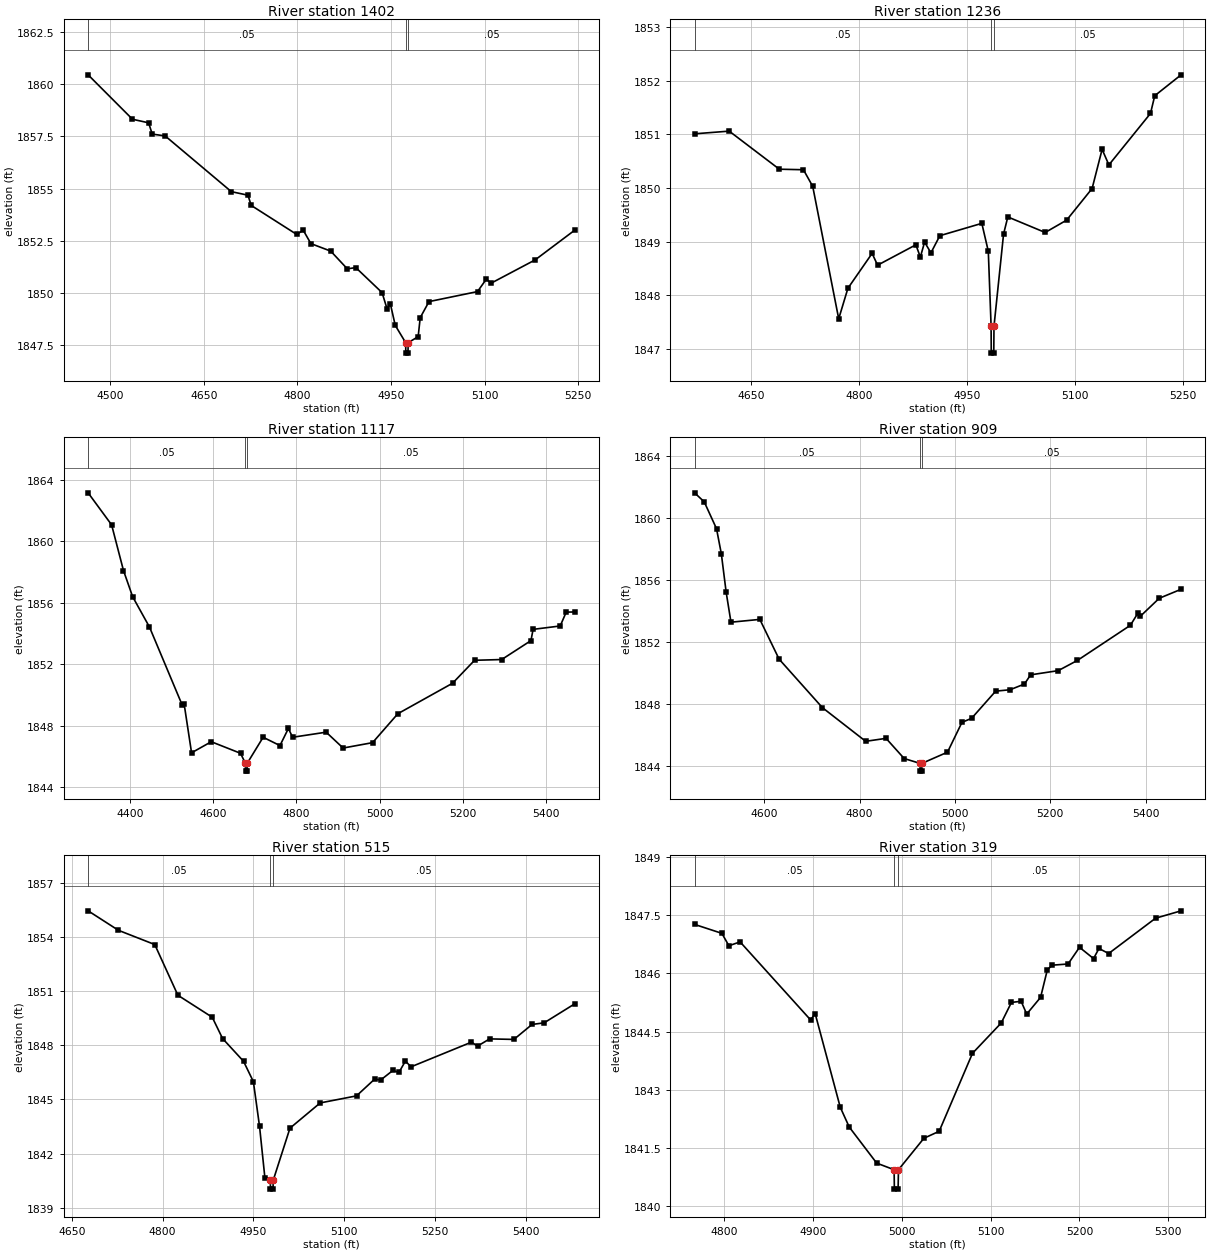
Type RM Length L Ch R = 1,1402,166,166,166
BEGIN DESCRIPTION:
Mapping XS a6600c76
END DESCRIPTION:
XS GIS Cut Line= 3
      1645320.01      6873730.41      1645155.31      6874232.89
      1645339.43      6874403.06
#Sta/Elev= 30
  4464.8 1860.45  4535.9 1858.32  4561.7 1858.15  4567.5 1857.61  4588.3 1857.52
  4694.3 1854.85  4720.9 1854.68  4726.1 1854.19  4799.0 1852.80  4809.5 1853.00
  4821.7 1852.36  4853.5 1852.00  4880.1 1851.15  4893.7 1851.21  4935.8 1850.01
  4943.8 1849.23  4949.0 1849.48  4956.9 1848.44  4973.6 1847.61  4973.8 1847.11
  4977.3 1847.11  4977.6 1847.61  4993.6 1847.90  4996.9 1848.81  5011.0 1849.58
  5088.7 1850.06  5102.9 1850.66  5110.3 1850.46  5181.1 1851.58  5244.3 1853.00
#Mann=3,-1,0
  4464.8    0.05       0  4973.6    0.05       0  4977.6    0.05       0
Bank Sta=4973.6,4977.6
Exp/Cntr=0.3,0.1

Type RM Length L Ch R = 1,1236,119,119,119
BEGIN DESCRIPTION:
Mapping XS 8f2a8cbc
END DESCRIPTION:
XS GIS Cut Line= 3
      1644830.82      6873921.34      1644904.61      6874216.50
      1645219.93      6874413.04
#Sta/Elev= 30
  4571.1 1851.01  4619.2 1851.06  4688.8 1850.35  4722.3 1850.34  4735.2 1850.03
  4771.3 1847.56  4784.1 1848.13  4817.7 1848.78  4825.3 1848.56  4878.5 1848.94
  4884.7 1848.71  4890.6 1848.99  4899.4 1848.79  4911.8 1849.11  4970.1 1849.34
  4979.1 1848.82  4983.0 1847.42  4983.2 1846.92  4986.7 1846.92  4987.0 1847.42
  5000.3 1849.14  5006.2 1849.46  5058.1 1849.17  5087.9 1849.40  5123.3 1849.99
  5137.2 1850.72  5146.6 1850.43  5204.4 1851.39  5210.3 1851.72  5246.9 1852.11
#Mann=3,-1,0
  4571.1    0.05       0  4983.0    0.03       0  4987.0    0.05       0
Bank Sta=4983,4987
Exp/Cntr=0.3,0.1

Type RM Length L Ch R = 1,1117,208,208,208
BEGIN DESCRIPTION:
Mapping XS 16a4d5c5
END DESCRIPTION:
XS GIS Cut Line= 2
      1644259.22      6874280.35      1645414.95      6874447.85
#Sta/Elev= 30
  4300.1 1863.14  4356.5 1861.06  4385.0 1858.09  4407.0 1856.39  4447.4 1854.42
  4525.5 1849.38  4530.5 1849.44  4548.4 1846.25  4595.7 1846.97  4665.9 1846.22
  4677.8 1845.56  4678.1 1845.06  4681.6 1845.06  4681.8 1845.56  4720.2 1847.26
  4760.6 1846.72  4780.8 1847.83  4791.0 1847.26  4871.5 1847.59  4912.2 1846.56
  4982.9 1846.91  5043.6 1848.79  5174.9 1850.77  5227.7 1852.26  5292.9 1852.31
  5363.1 1853.54  5368.2 1854.27  5433.3 1854.49  5447.7 1855.39  5467.9 1855.40
#Mann=3,-1,0
  4300.1    0.05       0  4677.8    0.05       0  4681.8    0.05       0
Bank Sta=4677.8,4681.8
Exp/Cntr=0.3,0.1

Type RM Length L Ch R = 1,909,394,394,394
BEGIN DESCRIPTION:
Mapping XS 2708393d
END DESCRIPTION:
XS GIS Cut Line= 2
      1644269.39      6874460.42      1645280.38      6874594.93
#Sta/Elev= 30
  4454.2 1861.60  4474.4 1861.02  4500.2 1859.29  4510.3 1857.67  4520.4 1855.20
  4530.5 1853.27  4591.0 1853.45  4631.4 1850.89  4722.1 1847.77  4812.9 1845.60
  4855.6 1845.79  4893.6 1844.49  4926.8 1844.18  4927.1 1843.68  4930.6 1843.68
  4930.8 1844.18  4984.4 1844.90  5014.7 1846.82  5034.9 1847.08  5085.4 1848.83
  5115.6 1848.92  5145.8 1849.29  5158.6 1849.88  5216.5 1850.15  5256.8 1850.81
  5367.8 1853.07  5383.3 1853.84  5388.3 1853.64  5428.3 1854.81  5474.1 1855.39
#Mann=3,-1,0
  4454.2    0.05       0  4926.8    0.05       0  4930.8    0.05       0
Bank Sta=4926.8,4930.8
Exp/Cntr=0.3,0.1

Type RM Length L Ch R = 1,515,196,196,196
BEGIN DESCRIPTION:
Mapping XS 11adda26
END DESCRIPTION:
XS GIS Cut Line= 3
      1644286.79      6874764.25      1644577.54      6874820.66
      1645085.37      6874803.30
#Sta/Elev= 30
  4676.8 1855.46  4726.9 1854.38  4787.0 1853.59  4825.2 1850.78  4882.0 1849.56
  4899.1 1848.38  4933.7 1847.12  4950.0 1845.99  4960.2 1843.51  4969.1 1840.64
  4978.0 1840.53  4978.3 1840.03  4982.5 1840.03  4982.9 1840.53  5010.5 1843.41
  5060.5 1844.81  5120.5 1845.20  5150.5 1846.13  5160.5 1846.08  5180.6 1846.61
  5190.6 1846.50  5201.4 1847.13  5210.6 1846.81  5310.6 1848.18  5320.6 1847.96
  5340.6 1848.36  5380.7 1848.33  5410.7 1849.16  5430.7 1849.25  5481.1 1850.30
#Mann=3,-1,0
  4676.8    0.05       0  4978.0    0.05       0  4982.9    0.05       0
Bank Sta=4978,4982.9
Exp/Cntr=0.3,0.1

Type RM Length L Ch R = 1,319,270,270,270
BEGIN DESCRIPTION:
Mapping XS 1d286eb1
END DESCRIPTION:
XS GIS Cut Line= 3
      1644425.03      6875052.00      1644648.53      6875002.09
      1644939.48      6874872.78
#Sta/Elev= 30
  4767.0 1847.26  4797.7 1847.03  4805.6 1846.71  4818.2 1846.81  4897.5 1844.80
  4902.7 1844.96  4930.9 1842.55  4941.0 1842.04  4971.9 1841.11  4991.5 1840.94
  4991.8 1840.44  4996.0 1840.44  4996.4 1840.94  5025.0 1841.75  5042.2 1841.93
  5079.7 1843.94  5112.0 1844.72  5123.5 1845.25  5134.4 1845.28  5140.7 1844.95
  5156.3 1845.38  5163.9 1846.09  5169.4 1846.21  5187.2 1846.24  5200.1 1846.67
  5215.9 1846.38  5222.0 1846.64  5232.9 1846.51  5285.7 1847.42  5314.4 1847.61
#Mann=3,-1,0
  4767.0    0.05       0  4991.5    0.05       0  4996.4    0.05       0
Bank Sta=4991.5,4996.4
Exp/Cntr=0.3,0.1

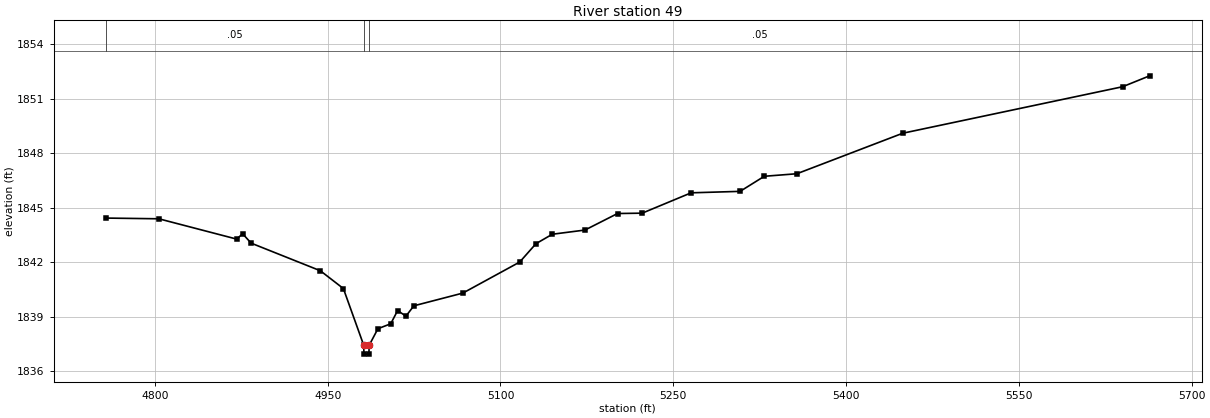
Type RM Length L Ch R = 1,49,0,0,0
BEGIN DESCRIPTION:
Deadman 47 1.0
END DESCRIPTION:
XS GIS Cut Line= 3
      1644508.98      6875227.00      1644751.36      6875239.51
      1645232.18      6874782.30
#Sta/Elev= 30
  4757.3 1844.44  4803.4 1844.40  4871.1 1843.28  4876.1 1843.58  4883.5 1843.06
  4943.6 1841.54  4963.6 1840.56  4981.2 1837.45  4981.5 1836.95  4985.7 1836.95
  4986.1 1837.45  4993.6 1838.35  5004.7 1838.62  5010.7 1839.35  5017.9 1839.04
  5024.8 1839.61  5067.3 1840.31  5116.7 1842.02  5130.8 1843.03  5145.0 1843.55
  5173.3 1843.78  5201.6 1844.69  5223.0 1844.71  5265.5 1845.83  5308.0 1845.91
  5329.0 1846.74  5357.3 1846.88  5449.2 1849.11  5640.1 1851.67  5663.5 1852.27
#Mann=3,-1,0
  4757.3    0.05       0  4981.2    0.05       0  4986.1    0.05       0
Bank Sta=4981.2,4986.1
Exp/Cntr=0.3,0.1

Chan Stop Cuts=-1