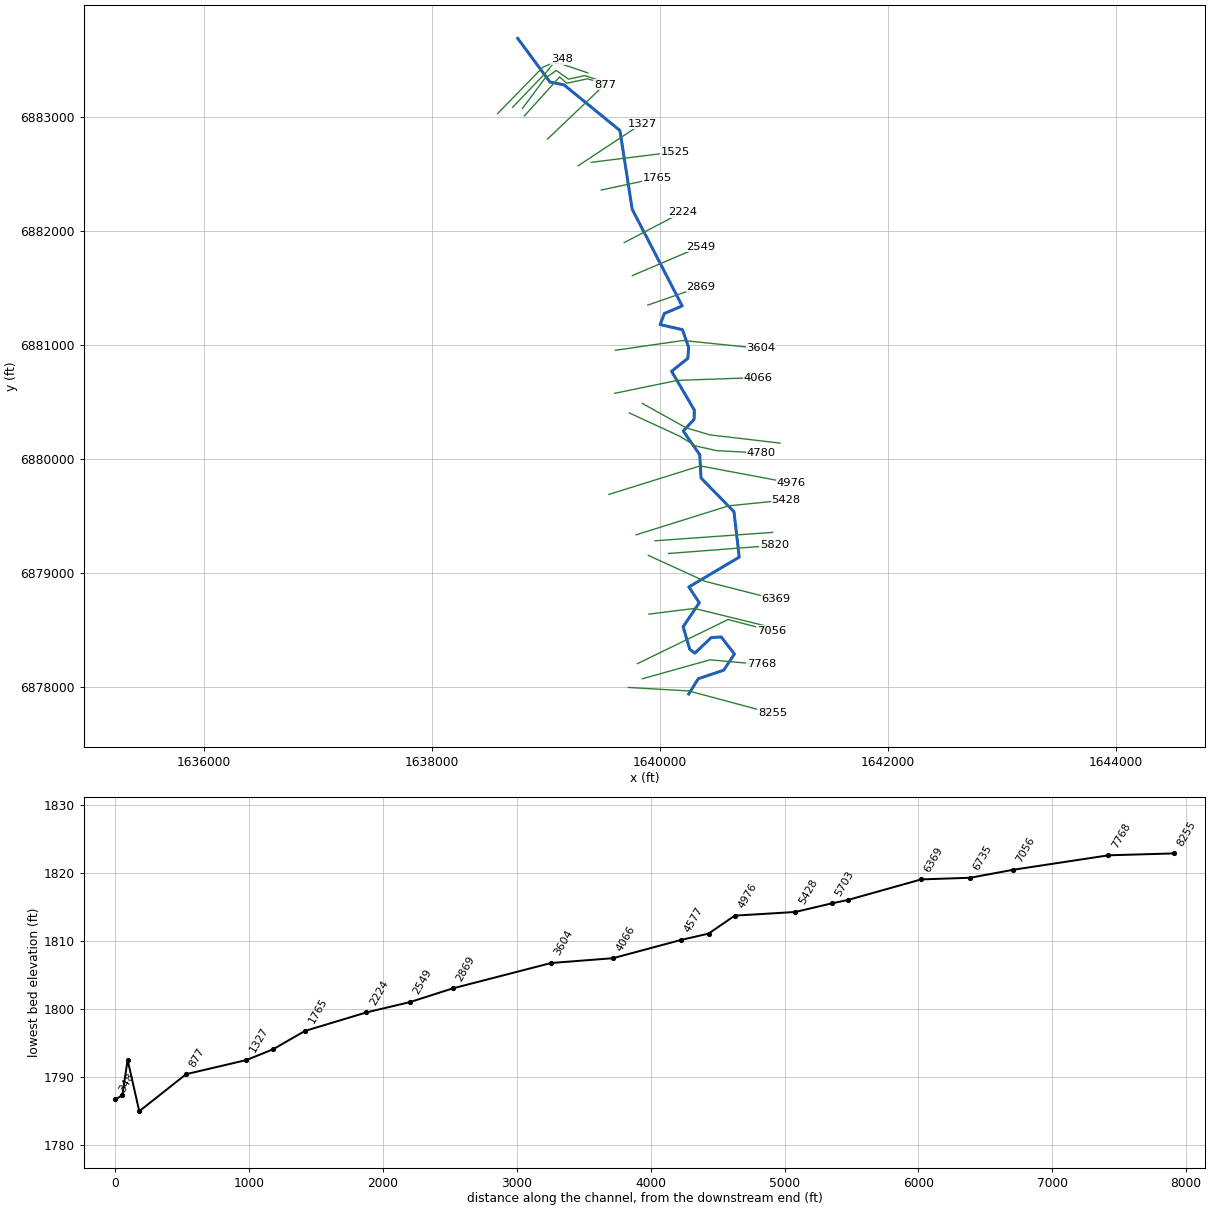
--- Deadman 48.prj (project) ---

Proj Title=Deadman 48 Base Level Engineering
Current Plan=p01
Default Exp/Contr=0.3,0.1
English Units
Geom File=g01
Flow File=f01
Plan File=p01
BEGIN DESCRIPTION:
Deadman 48
END DESCRIPTION:

--- Deadman 48.p01 (plan) ---

Plan Title=Multiple Run
Short Identifier=Multiple
Geom File=g01
Flow File=f01
Subcritical Flow
K Sum by GR= 0
Std Step Tol= 0.01
Critical Tol= 0.01
Num of Std Step Trials= 20
Max Error Tol= 0.3
Flow Tol Ratio= 0.001
Split Flow NTrial= 30
Split Flow Tol= 0.02
Split Flow Ratio= 0.02
Log Output Level= 0
Friction Slope Method= 1
Unsteady Friction Slope Method= 2
Unsteady Bridges Friction Slope Method= 1
Parabolic Critical Depth
Global Vel Dist=  1 , 1 , 1
Global Log Level= 0
CheckData=True
Encroach Param= -1, 0, 0, 0
BEGIN DESCRIPTION:
Multiple Run
END DESCRIPTION:

--- Deadman 48.f01 (steady flow) ---

Flow Title=Multiple
Number of Profiles=7
Profile Names=10-year,25-year,50-year,1pct_min,100-year,1pct_plu,500-year
River Rch & RM= Deadman 48,Reach-1,8255
     244     333     405     245     490     977     724
Boundary for River Rch & Prof#=Deadman 48,Reach-1,1
Up Type=0
Dn Type=3
Dn Slope=0.007
Boundary for River Rch & Prof#=Deadman 48,Reach-1,2
Up Type=0
Dn Type=3
Dn Slope=0.007
Boundary for River Rch & Prof#=Deadman 48,Reach-1,3
Up Type=0
Dn Type=3
Dn Slope=0.007
Boundary for River Rch & Prof#=Deadman 48,Reach-1,4
Up Type=0
Dn Type=3
Dn Slope=0.007
Boundary for River Rch & Prof#=Deadman 48,Reach-1,5
Up Type=0
Dn Type=3
Dn Slope=0.007
Boundary for River Rch & Prof#=Deadman 48,Reach-1,6
Up Type=0
Dn Type=3
Dn Slope=0.007
Boundary for River Rch & Prof#=Deadman 48,Reach-1,7
Up Type=0
Dn Type=3
Dn Slope=0.007

--- Deadman 48.g01 (geometry) ---

Geom Title=Existing Conditions

River Reach=Deadman 48,Reach-1
Reach XY= 30
      1640255.00      6877938.00      1640338.29      6878071.38
      1640561.19      6878145.85      1640655.88      6878288.00
      1640539.79      6878437.77      1640452.57      6878432.60
      1640308.15      6878295.51      1640263.14      6878331.28
      1640205.94      6878527.52      1640347.70      6878738.08
      1640256.13      6878875.97      1640697.68      6879137.87
      1640651.46      6879536.54      1640362.81      6879831.81
      1640351.25      6880036.45      1640206.57      6880244.09
      1640302.00      6880346.35      1640304.11      6880427.41
      1640104.55      6880767.97      1640247.36      6880881.55
      1640253.90      6880977.44      1640199.92      6881132.97
      1640003.94      6881177.45      1640041.26      6881274.76
      1640197.48      6881341.12      1639758.75      6882189.55
      1639651.49      6882879.52      1639161.17      6883280.14
      1639037.87      6883304.30      1638755.00      6883688.00

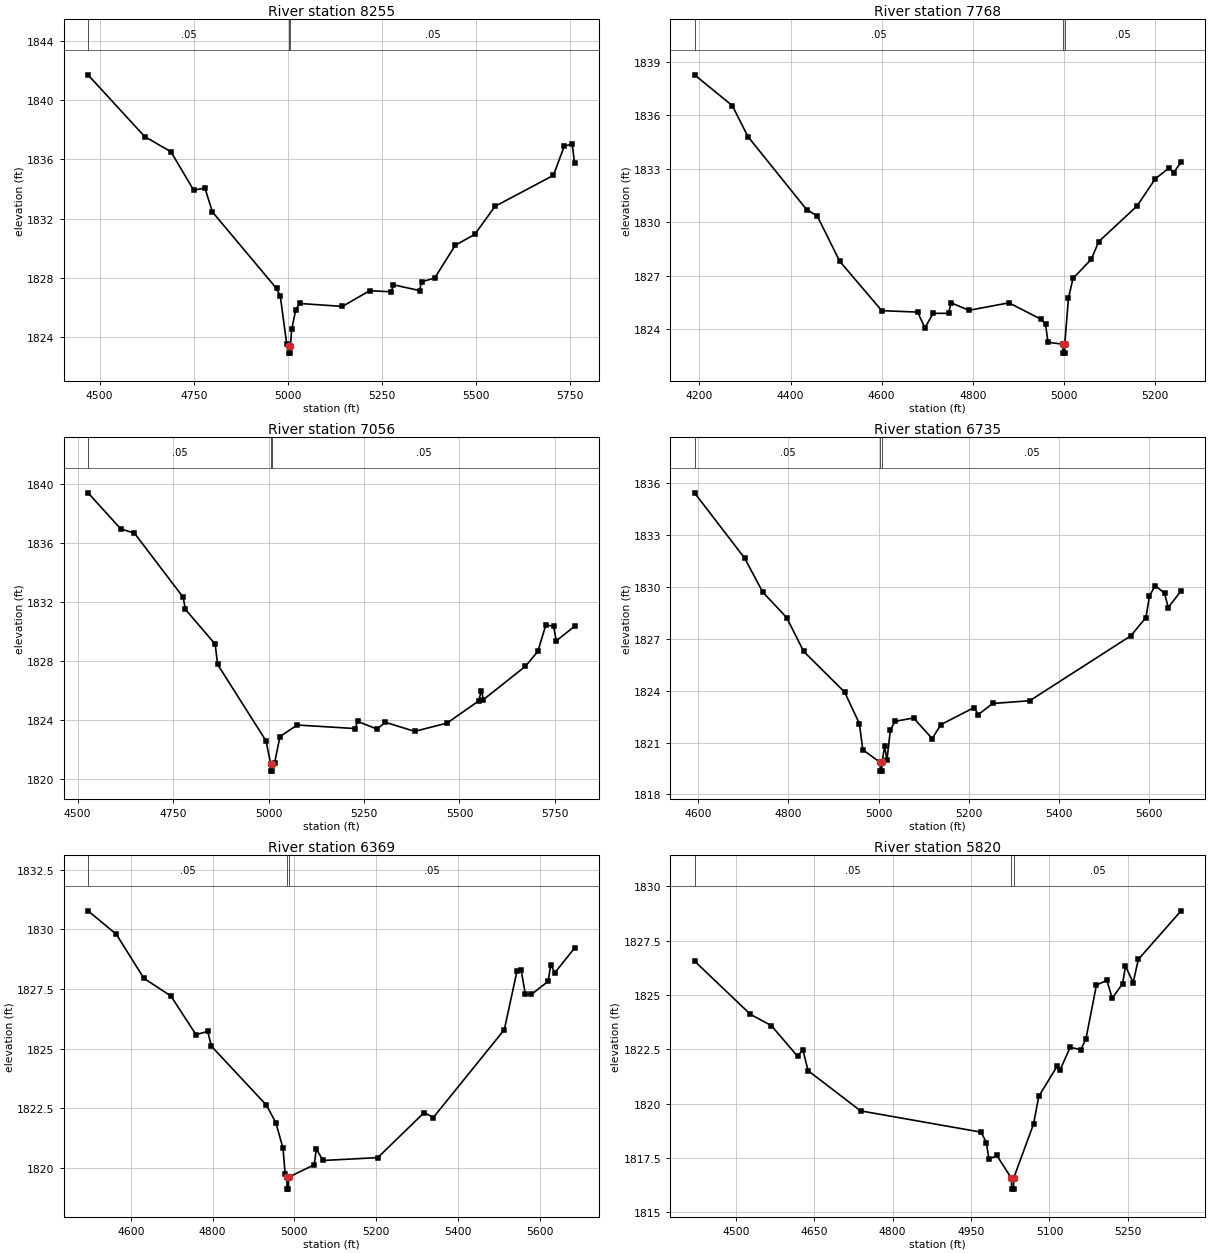
Type RM Length L Ch R = 1,8255,487,487,487
BEGIN DESCRIPTION:
Deadman 48 9.0
END DESCRIPTION:
XS GIS Cut Line= 3
      1639724.86      6877995.16      1640254.09      6877964.31
      1640991.07      6877767.62
#Sta/Elev= 30
  4469.0 1841.71  4619.4 1837.55  4689.5 1836.52  4749.6 1833.94  4779.7 1834.07
  4799.7 1832.46  4970.0 1827.30  4980.0 1826.78  4997.1 1823.54  5002.7 1823.44
  5003.0 1822.94  5006.5 1822.94  5006.7 1823.44  5010.4 1824.56  5020.8 1825.83
  5031.1 1826.29  5145.0 1826.09  5217.4 1827.15  5275.0 1827.08  5280.2 1827.55
  5350.0 1827.16  5355.2 1827.75  5390.1 1828.00  5445.1 1830.22  5496.9 1830.95
  5550.5 1832.84  5705.7 1834.93  5734.9 1836.92  5755.6 1837.02  5761.9 1835.77
#Mann=3,-1,0
  4469.0    0.05       0  5002.7    0.05       0  5006.7    0.05       0
Bank Sta=5002.7,5006.7
Exp/Cntr=0.3,0.1

Type RM Length L Ch R = 1,7768,712,712,712
BEGIN DESCRIPTION:
Mapping XS 61adac8f
END DESCRIPTION:
XS GIS Cut Line= 3
      1639848.31      6878071.12      1640441.58      6878237.23
      1640891.20      6878197.00
#Sta/Elev= 30
  4189.4 1838.26  4272.4 1836.53  4306.5 1834.80  4435.2 1830.71  4458.6 1830.35
  4507.9 1827.81  4600.2 1825.04  4678.9 1824.96  4694.8 1824.08  4713.0 1824.89
  4746.7 1824.89  4752.3 1825.48  4791.6 1825.06  4879.2 1825.48  4949.5 1824.56
  4959.5 1824.28  4964.9 1823.27  4997.7 1823.16  4997.9 1822.66  5001.4 1822.66
  5001.7 1823.16  5009.7 1825.73  5019.8 1826.85  5059.9 1827.92  5076.2 1828.91
  5160.3 1830.91  5200.5 1832.44  5230.6 1833.04  5240.6 1832.78  5256.9 1833.37
#Mann=3,-1,0
  4189.4    0.05       0  4997.7    0.05       0  5001.7    0.05       0
Bank Sta=4997.7,5001.7
Exp/Cntr=0.3,0.1

Type RM Length L Ch R = 1,7056,321,321,321
BEGIN DESCRIPTION:
Mapping XS 194ebee1
END DESCRIPTION:
XS GIS Cut Line= 3
      1639805.59      6878204.03      1640600.59      6878590.84
      1640977.94      6878491.17
#Sta/Elev= 30
  4527.1 1839.42  4613.0 1836.97  4648.8 1836.68  4776.4 1832.33  4782.2 1831.51
  4860.1 1829.15  4866.6 1827.77  4993.5 1822.58  5005.5 1821.03  5005.7 1820.53
  5009.2 1820.53  5009.5 1821.03  5015.8 1821.09  5030.0 1822.88  5075.1 1823.66
  5227.1 1823.42  5233.0 1823.91  5283.6 1823.39  5306.2 1823.84  5382.8 1823.23
  5467.5 1823.79  5550.2 1825.29  5557.4 1826.00  5562.6 1825.38  5673.0 1827.65
  5705.4 1828.66  5726.1 1830.44  5746.7 1830.37  5753.5 1829.37  5801.5 1830.36
#Mann=3,-1,0
  4527.1    0.05       0  5005.5    0.05       0  5009.5    0.05       0
Bank Sta=5005.5,5009.5
Exp/Cntr=0.3,0.1

Type RM Length L Ch R = 1,6735,366,366,366
BEGIN DESCRIPTION:
Deadman 48 8.0
END DESCRIPTION:
XS GIS Cut Line= 3
      1639905.00      6878638.00      1640305.00      6878688.00
      1640960.69      6878526.92
#Sta/Elev= 30
  4591.9 1835.44  4702.8 1831.67  4743.1 1829.70  4796.0 1828.23  4833.8 1826.27
  4924.5 1823.92  4957.2 1822.10  4964.8 1820.59  5003.3 1819.85  5003.6 1819.35
  5007.1 1819.35  5007.3 1819.85  5013.2 1820.78  5018.4 1820.00  5025.9 1821.72
  5036.2 1822.23  5077.4 1822.42  5118.6 1821.23  5137.9 1822.04  5211.3 1823.02
  5221.0 1822.62  5252.4 1823.26  5334.8 1823.42  5558.6 1827.17  5592.3 1828.23
  5600.1 1829.47  5612.9 1830.08  5633.5 1829.63  5641.7 1828.81  5670.2 1829.77
#Mann=3,-1,0
  4591.9    0.05       0  5003.3    0.05       0  5007.3    0.05       0
Bank Sta=5003.3,5007.3
Exp/Cntr=0.3,0.1

Type RM Length L Ch R = 1,6369,549,549,549
BEGIN DESCRIPTION:
Deadman 48 7.0
END DESCRIPTION:
XS GIS Cut Line= 3
      1639900.45      6879153.31      1640398.86      6878925.47
      1641021.56      6878766.84
#Sta/Elev= 30
  4495.1 1830.77  4564.3 1829.79  4632.0 1827.94  4698.0 1827.20  4759.5 1825.58
  4788.0 1825.72  4797.0 1825.10  4931.6 1822.63  4954.6 1821.90  4972.2 1820.83
  4977.6 1819.74  4981.8 1819.61  4982.1 1819.11  4985.7 1819.11  4985.9 1819.61
  5048.7 1820.13  5053.9 1820.79  5070.1 1820.31  5204.2 1820.43  5317.8 1822.32
  5340.1 1822.11  5513.8 1825.79  5544.8 1828.24  5555.1 1828.27  5565.4 1827.27
  5580.3 1827.27  5621.2 1827.82  5627.3 1828.51  5637.7 1828.18  5685.7 1829.21
#Mann=3,-1,0
  4495.1    0.05       0  4981.8    0.05       0  4985.9    0.05       0
Bank Sta=4981.8,4985.9
Exp/Cntr=0.3,0.1

Type RM Length L Ch R = 1,5820,117,117,117
BEGIN DESCRIPTION:
Mapping XS 7efdd99d
END DESCRIPTION:
XS GIS Cut Line= 2
      1640078.45      6879169.91      1641006.42      6879241.11
#Sta/Elev= 30
  4421.1 1826.56  4528.0 1824.11  4568.1 1823.59  4618.2 1822.18  4628.3 1822.48
  4638.3 1821.52  4738.6 1819.67  4969.3 1818.69  4979.3 1818.21  4984.3 1817.44
  4999.3 1817.62  5027.3 1816.57  5027.6 1816.07  5031.3 1816.07  5031.5 1816.57
  5069.5 1819.06  5079.6 1820.34  5114.9 1821.73  5119.9 1821.53  5139.8 1822.60
  5159.8 1822.48  5169.8 1822.98  5189.9 1825.46  5210.0 1825.67  5220.0 1824.85
  5240.0 1825.52  5245.4 1826.33  5260.1 1825.57  5270.1 1826.64  5351.8 1828.87
#Mann=3,-1,0
  4421.1    0.05       0  5027.3    0.05       0  5031.5    0.05       0
Bank Sta=5027.3,5031.5
Exp/Cntr=0.3,0.1

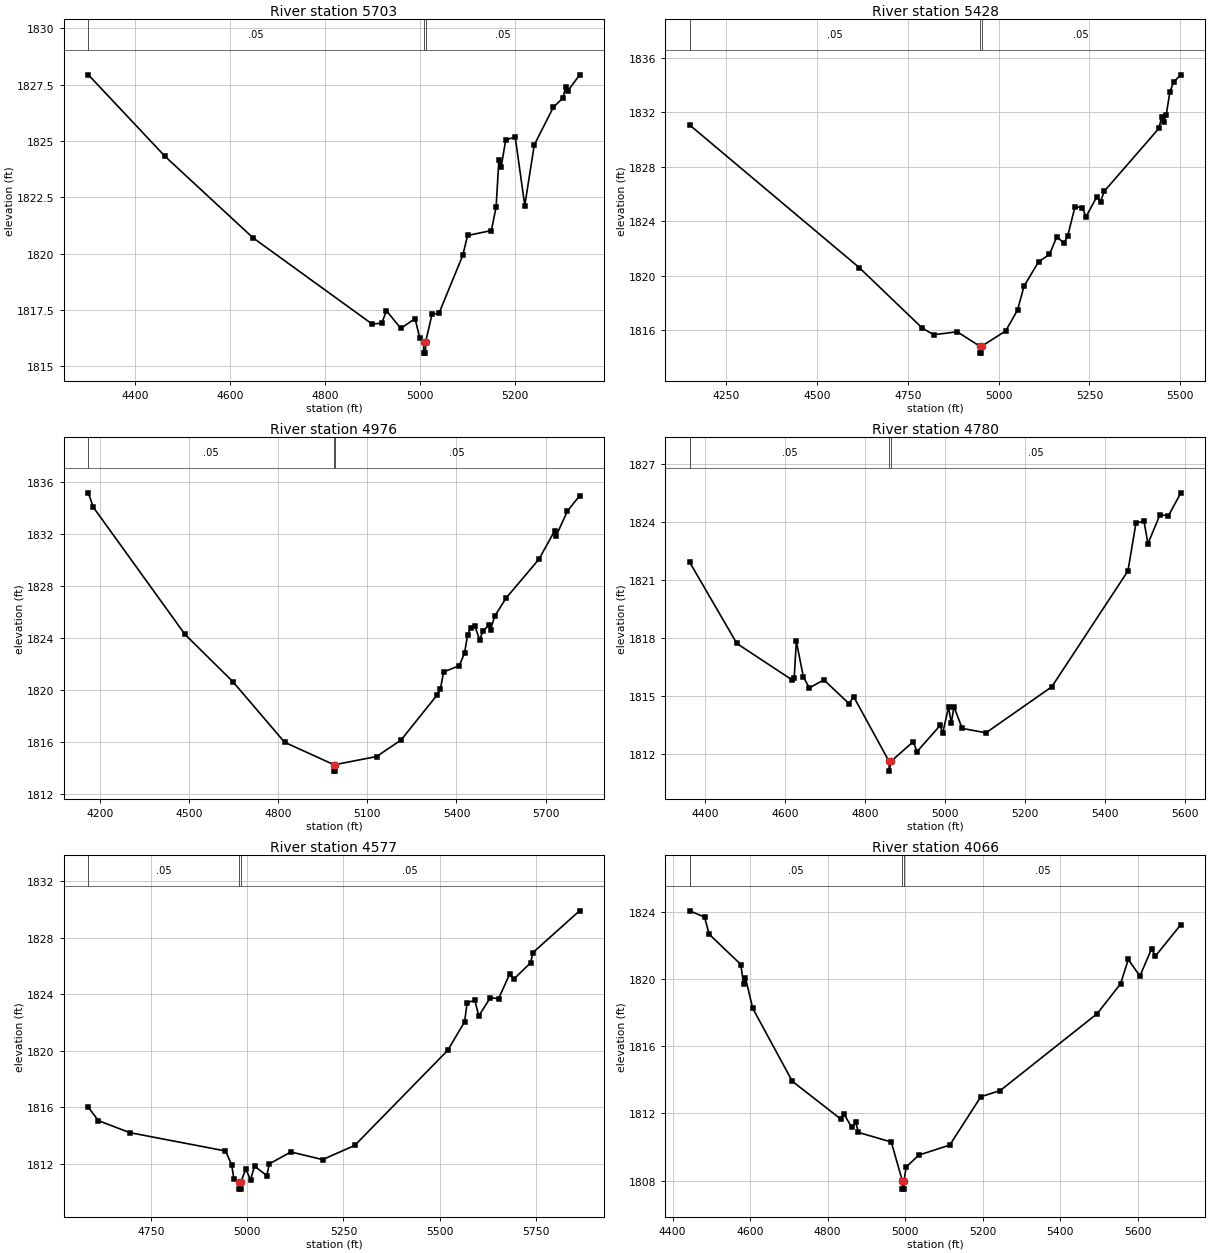
Type RM Length L Ch R = 1,5703,275,275,275
BEGIN DESCRIPTION:
Mapping XS b81c9726
END DESCRIPTION:
XS GIS Cut Line= 2
      1639959.84      6879281.46      1640989.81      6879355.03
#Sta/Elev= 30
  4302.5 1827.94  4463.8 1824.32  4648.5 1820.71  4899.2 1816.88  4919.2 1816.92
  4929.3 1817.47  4959.3 1816.69  4989.4 1817.12  4999.4 1816.24  5007.4 1816.09
  5007.6 1815.59  5011.3 1815.59  5011.6 1816.09  5025.2 1817.33  5039.5 1817.35
  5089.7 1819.93  5099.7 1820.81  5149.8 1821.03  5159.8 1822.08  5165.6 1824.17
  5170.6 1823.87  5179.9 1825.05  5199.9 1825.18  5220.0 1822.14  5240.0 1824.83
  5280.1 1826.50  5300.2 1826.91  5305.9 1827.38  5310.9 1827.24  5335.1 1827.93
#Mann=3,-1,0
  4302.5    0.05       0  5007.4    0.03       0  5011.6    0.05       0
Bank Sta=5007.4,5011.6
Exp/Cntr=0.3,0.1

Type RM Length L Ch R = 1,5428,452,452,452
BEGIN DESCRIPTION:
Deadman 48 6.0
END DESCRIPTION:
XS GIS Cut Line= 3
      1639793.73      6879333.68      1640605.00      6879588.00
      1641105.00      6879638.00
#Sta/Elev= 30
  4149.1 1831.07  4615.8 1820.60  4789.7 1816.15  4821.1 1815.66  4885.8 1815.88
  4948.5 1814.81  4948.8 1814.31  4952.5 1814.31  4952.8 1814.81  5019.4 1815.94
  5052.1 1817.48  5069.7 1819.22  5109.8 1821.02  5140.0 1821.56  5160.1 1822.86
  5180.2 1822.39  5190.2 1822.93  5210.3 1825.07  5230.4 1825.00  5240.5 1824.33
  5270.6 1825.81  5280.7 1825.45  5290.7 1826.20  5441.5 1830.83  5449.0 1831.69
  5454.1 1831.32  5461.6 1831.83  5471.6 1833.51  5481.7 1834.23  5501.8 1834.76
#Mann=3,-1,0
  4149.1    0.05       0  4948.5    0.05       0  4952.8    0.05       0
Bank Sta=4948.5,4952.8
Exp/Cntr=0.3,0.1

Type RM Length L Ch R = 1,4976,196,196,196
BEGIN DESCRIPTION:
Deadman 48 5.0
END DESCRIPTION:
XS GIS Cut Line= 3
      1639555.03      6879688.01      1640355.00      6879938.00
      1641155.03      6879787.99
#Sta/Elev= 30
  4161.7 1835.15  4177.9 1834.06  4486.5 1824.28  4648.3 1820.63  4821.7 1815.99
  4987.1 1814.27  4987.4 1813.77  4991.2 1813.77  4991.5 1814.27  5131.2 1814.89
  5213.5 1816.16  5335.6 1819.64  5345.7 1820.08  5356.8 1821.39  5409.3 1821.87
  5427.1 1822.84  5437.3 1824.22  5447.5 1824.77  5461.9 1824.91  5478.0 1823.84
  5488.2 1824.53  5508.5 1824.96  5514.5 1824.65  5528.9 1825.69  5567.0 1827.07
  5677.3 1830.05  5729.8 1832.21  5734.9 1831.83  5773.1 1833.75  5813.8 1834.92
#Mann=3,-1,0
  4161.7    0.05       0  4987.1    0.05       0  4991.5    0.05       0
Bank Sta=4987.1,4991.5
Exp/Cntr=0.3,0.1

Type RM Length L Ch R = 1,4780,203,203,203
BEGIN DESCRIPTION:
Mapping XS 351a55f7
END DESCRIPTION:
XS GIS Cut Line= 5
      1639733.54      6880402.67      1640173.60      6880199.57
      1640314.23      6880113.63      1640499.13      6880071.96
      1640887.15      6880051.13
#Sta/Elev= 30
  4361.5 1821.92  4479.4 1817.72  4616.4 1815.85  4622.6 1815.91  4628.1 1817.83
  4645.5 1816.00  4660.5 1815.42  4696.9 1815.84  4759.6 1814.61  4771.3 1814.97
  4859.9 1811.62  4860.2 1811.12  4864.3 1811.62  4920.1 1812.64  4929.7 1812.13
  4987.8 1813.49  4993.7 1813.07  5008.5 1814.43  5015.4 1813.60  5022.0 1814.45
  5042.5 1813.33  5101.9 1813.10  5266.5 1815.48  5456.8 1821.47  5476.8 1823.93
  5496.8 1824.06  5506.8 1822.88  5536.9 1824.38  5558.0 1824.32  5589.1 1825.51
#Mann=3,-1,0
  4361.5    0.05       0  4859.9    0.05       0  4864.3    0.05       0
Bank Sta=4859.9,4864.3
Exp/Cntr=0.3,0.1

Type RM Length L Ch R = 1,4577,511,511,511
BEGIN DESCRIPTION:
Deadman 48 4.0
END DESCRIPTION:
XS GIS Cut Line= 4
      1639848.06      6880486.04      1640230.90      6880272.48
      1640441.83      6880209.98      1641054.95      6880138.01
#Sta/Elev= 30
  4587.4 1815.99  4613.3 1815.05  4694.5 1814.20  4943.6 1812.90  4959.6 1811.93
  4965.3 1810.94  4979.1 1810.70  4979.4 1810.20  4983.2 1810.20  4983.5 1810.70
  4996.1 1811.62  5008.7 1810.86  5019.0 1811.82  5050.9 1811.16  5057.6 1811.99
  5113.5 1812.83  5195.8 1812.29  5279.2 1813.29  5520.8 1820.02  5564.5 1822.03
  5571.2 1823.39  5591.3 1823.56  5601.4 1822.45  5631.6 1823.75  5652.7 1823.67
  5681.9 1825.42  5692.0 1825.05  5735.9 1826.21  5742.3 1826.94  5863.1 1829.89
#Mann=3,-1,0
  4587.4    0.05       0  4979.1    0.03       0  4983.5    0.05       0
Bank Sta=4979.1,4983.5
Exp/Cntr=0.3,0.1

Type RM Length L Ch R = 1,4066,462,462,462
BEGIN DESCRIPTION:
Deadman 48 3.0
END DESCRIPTION:
XS GIS Cut Line= 3
      1639605.88      6880574.56      1640155.00      6880688.00
      1640860.55      6880712.57
#Sta/Elev= 30
  4444.2 1824.04  4482.5 1823.67  4494.4 1822.65  4576.1 1820.85  4583.0 1819.68
  4588.1 1820.05  4606.7 1818.25  4708.8 1813.91  4834.2 1811.66  4841.5 1811.98
  4862.0 1811.18  4872.2 1811.48  4879.3 1810.87  4964.1 1810.30  4992.5 1808.00
  4992.8 1807.50  4996.7 1807.50  4997.0 1808.00  5002.4 1808.81  5034.9 1809.52
  5115.0 1810.12  5195.0 1812.99  5245.1 1813.36  5495.2 1817.93  5555.3 1819.70
  5575.3 1821.15  5605.3 1820.16  5635.3 1821.78  5645.3 1821.35  5710.9 1823.22
#Mann=3,-1,0
  4444.2    0.05       0  4992.5    0.03       0  4997.0    0.05       0
Bank Sta=4992.5,4997
Exp/Cntr=0.3,0.1

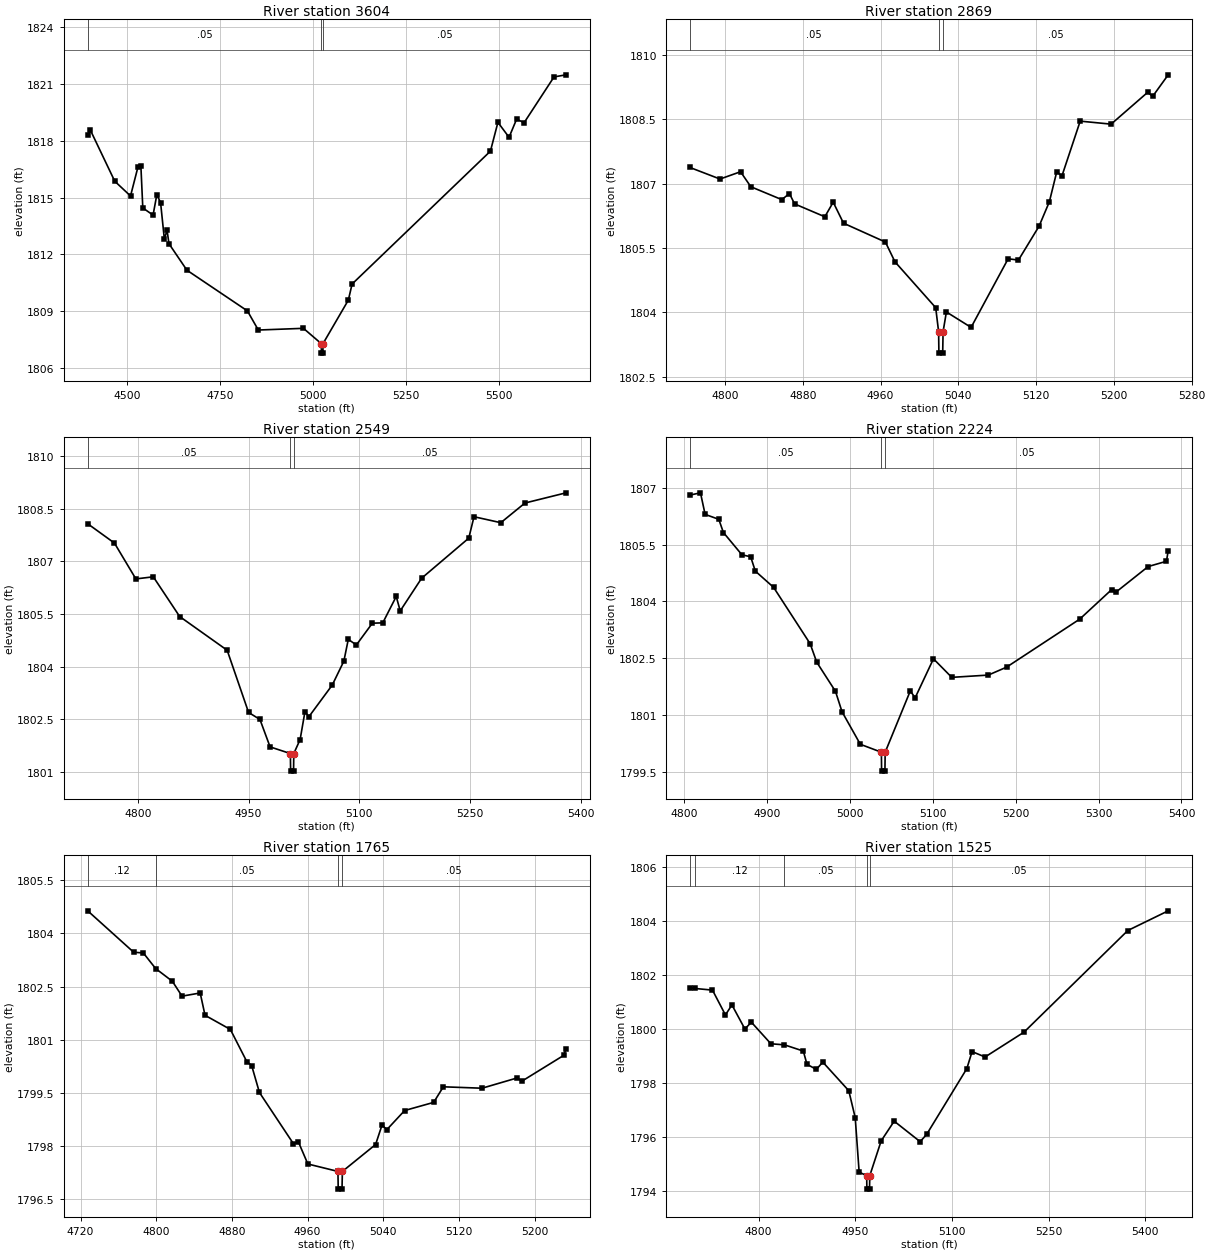
Type RM Length L Ch R = 1,3604,735,735,735
BEGIN DESCRIPTION:
Deadman 48 2.0
END DESCRIPTION:
XS GIS Cut Line= 3
      1639611.09      6880952.17      1640205.00      6881038.00
      1640887.12      6880967.80
#Sta/Elev= 30
  4394.1 1818.29  4401.5 1818.56  4466.8 1815.87  4509.2 1815.09  4529.4 1816.64
  4537.1 1816.65  4542.2 1814.46  4569.8 1814.08  4579.9 1815.16  4590.0 1814.74
  4600.1 1812.82  4607.4 1813.28  4612.5 1812.57  4660.8 1811.17  4823.4 1809.02
  4852.7 1808.01  4974.0 1808.10  5022.1 1807.29  5022.4 1806.79  5026.3 1806.79
  5026.6 1807.29  5094.7 1809.59  5104.8 1810.44  5476.7 1817.46  5496.8 1818.98
  5526.7 1818.19  5547.1 1819.15  5567.2 1818.96  5647.6 1821.38  5679.9 1821.49
#Mann=3,-1,0
  4394.1    0.05       0  5022.1    0.05       0  5026.6    0.05       0
Bank Sta=5022.1,5026.6
Exp/Cntr=0.3,0.1

Type RM Length L Ch R = 1,2869,320,320,320
BEGIN DESCRIPTION:
Mapping XS 5c919825
END DESCRIPTION:
XS GIS Cut Line= 2
      1639895.76      6881348.56      1640360.48      6881509.79
#Sta/Elev= 30
  4763.9 1807.38  4794.9 1807.11  4816.0 1807.28  4826.6 1806.93  4858.4 1806.63
  4866.3 1806.77  4871.6 1806.53  4902.7 1806.23  4911.3 1806.57  4921.9 1806.08
  4965.0 1805.64  4974.8 1805.18  5016.7 1804.11  5019.7 1803.55  5020.0 1803.05
  5023.9 1803.05  5024.3 1803.55  5027.7 1804.01  5053.1 1803.65  5091.2 1805.25
  5101.8 1805.22  5123.0 1806.01  5133.6 1806.58  5141.2 1807.28  5146.5 1807.18
  5165.3 1808.46  5197.1 1808.39  5234.6 1809.13  5239.9 1809.04  5255.8 1809.54
#Mann=3,-1,0
  4763.9    0.05       0  5019.7    0.05       0  5024.3    0.05       0
Bank Sta=5019.7,5024.3
Exp/Cntr=0.3,0.1

Type RM Length L Ch R = 1,2549,325,325,325
BEGIN DESCRIPTION:
Mapping XS 383040ba
END DESCRIPTION:
XS GIS Cut Line= 2
      1639760.46      6881607.23      1640356.19      6881861.19
#Sta/Elev= 30
  4732.3 1808.07  4768.5 1807.52  4797.5 1806.50  4821.1 1806.56  4856.8 1805.43
  4921.1 1804.47  4950.1 1802.70  4965.5 1802.50  4979.2 1801.72  5006.7 1801.53
  5007.0 1801.03  5011.0 1801.03  5011.3 1801.53  5019.9 1801.93  5026.4 1802.72
  5031.8 1802.58  5063.4 1803.48  5079.1 1804.16  5085.1 1804.78  5096.0 1804.62
  5117.7 1805.24  5131.8 1805.25  5150.0 1806.00  5155.4 1805.59  5184.4 1806.52
  5248.2 1807.66  5255.3 1808.27  5291.6 1808.10  5324.3 1808.66  5379.9 1808.95
#Mann=3,-1,0
  4732.3    0.05       0  5006.7    0.05       0  5011.3    0.05       0
Bank Sta=5006.7,5011.3
Exp/Cntr=0.3,0.1

Type RM Length L Ch R = 1,2224,459,459,459
BEGIN DESCRIPTION:
Mapping XS 540b1a7f
END DESCRIPTION:
XS GIS Cut Line= 2
      1639689.24      6881896.76      1640200.95      6882164.46
#Sta/Elev= 30
  4806.5 1806.81  4819.3 1806.87  4824.9 1806.30  4841.4 1806.17  4847.0 1805.82
  4869.4 1805.23  4879.9 1805.18  4885.5 1804.80  4907.6 1804.37  4951.7 1802.88
  4959.7 1802.39  4982.3 1801.62  4990.2 1801.08  5012.3 1800.22  5037.7 1800.01
  5038.0 1799.51  5042.0 1799.51  5042.3 1800.01  5072.6 1801.63  5078.5 1801.45
  5100.6 1802.48  5122.7 1801.99  5166.8 1802.05  5188.9 1802.26  5277.2 1803.53
  5315.7 1804.31  5321.3 1804.25  5359.8 1804.92  5381.9 1805.06  5384.0 1805.34
#Mann=3,-1,0
  4806.5    0.05       0  5037.7    0.05       0  5042.3    0.05       0
Bank Sta=5037.7,5042.3
Exp/Cntr=0.3,0.1

Type RM Length L Ch R = 1,1765,240,240,240
BEGIN DESCRIPTION:
Mapping XS b0eaa362
END DESCRIPTION:
XS GIS Cut Line= 2
      1639487.54      6882357.18      1639981.81      6882463.60
#Sta/Elev= 30
  4727.6 1804.64  4776.2 1803.47  4786.4 1803.45  4799.4 1803.01  4817.1 1802.65
  4827.3 1802.23  4846.5 1802.32  4851.6 1801.69  4878.4 1801.29  4895.8 1800.38
  4900.9 1800.27  4909.1 1799.51  4945.1 1798.06  4950.2 1798.12  4960.3 1797.49
  4992.1 1797.28  4992.4 1796.78  4996.4 1796.78  4996.8 1797.28  5031.9 1798.04
  5038.7 1798.59  5043.8 1798.46  5062.6 1799.00  5093.3 1799.23  5103.5 1799.67
  5144.4 1799.63  5181.5 1799.92  5186.6 1799.83  5230.9 1800.56  5233.2 1800.75
#Mann=4,-1,0
  4727.6    0.12       0  4799.4    0.05       0  4992.1    0.05       0
  4996.8    0.05       0
Bank Sta=4992.1,4996.8
Exp/Cntr=0.3,0.1

Type RM Length L Ch R = 1,1525,198,198,198
BEGIN DESCRIPTION:
Mapping XS 3dd1b86f
END DESCRIPTION:
XS GIS Cut Line= 2
      1639400.20      6882600.61      1640137.18      6882691.76
#Sta/Elev= 30
  4693.2 1801.53  4701.5 1801.50  4728.3 1801.44  4748.4 1800.52  4758.5 1800.89
  4778.6 1800.00  4788.7 1800.25  4819.0 1799.45  4840.1 1799.41  4869.3 1799.18
  4875.0 1798.69  4889.5 1798.50  4899.6 1798.77  4939.9 1797.71  4949.9 1796.71
  4956.0 1794.69  4967.7 1794.56  4968.0 1794.06  4972.1 1794.06  4972.5 1794.56
  4990.2 1795.85  5010.4 1796.58  5050.7 1795.82  5060.8 1796.09  5123.2 1798.53
  5131.3 1799.16  5151.5 1798.96  5211.9 1799.88  5373.1 1803.65  5435.8 1804.38
#Mann=5,-1,0
  4693.2    0.05       0  4701.5    0.12       0  4840.1    0.05       0
  4967.7    0.05       0  4972.5    0.05       0
Bank Sta=4967.7,4972.5
Exp/Cntr=0.3,0.1

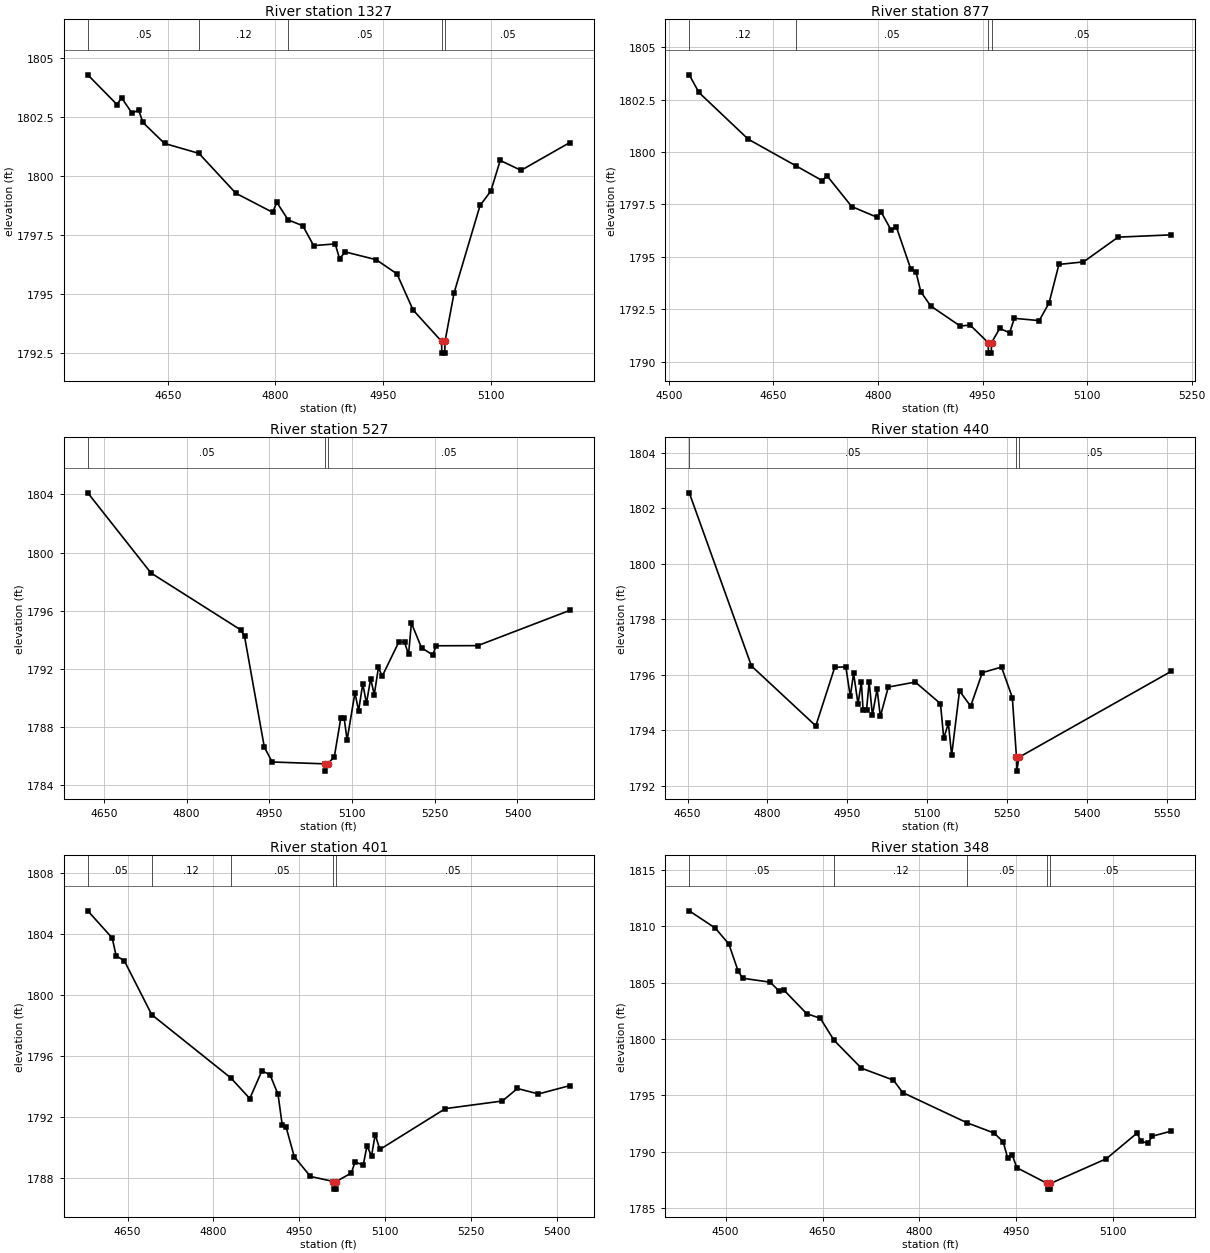
Type RM Length L Ch R = 1,1327,450,450,450
BEGIN DESCRIPTION:
Mapping XS 0f53f866
END DESCRIPTION:
XS GIS Cut Line= 2
      1639285.80      6882570.76      1639845.90      6882940.99
#Sta/Elev= 30
  4538.7 1804.29  4579.4 1803.03  4585.7 1803.32  4600.4 1802.66  4609.5 1802.80
  4615.5 1802.27  4645.6 1801.38  4693.5 1800.96  4744.9 1799.27  4796.1 1798.46
  4802.0 1798.88  4817.7 1798.14  4838.2 1797.89  4853.2 1797.05  4883.3 1797.12
  4889.3 1796.50  4897.4 1796.78  4940.5 1796.45  4969.3 1795.85  4991.7 1794.32
  5031.4 1792.99  5031.8 1792.49  5035.9 1792.49  5036.2 1792.99  5048.9 1795.05
  5085.0 1798.75  5100.0 1799.36  5113.1 1800.66  5142.1 1800.24  5210.1 1801.42
#Mann=5,-1,0
  4538.7    0.05       0  4693.5    0.12       0  4817.7    0.05       0
  5031.4    0.05       0  5036.2    0.05       0
Bank Sta=5031.4,5036.2
Exp/Cntr=0.3,0.1

Type RM Length L Ch R = 1,877,350,350,350
BEGIN DESCRIPTION:
Mapping XS cbfa2514
END DESCRIPTION:
XS GIS Cut Line= 2
      1639017.64      6882805.72      1639518.39      6883282.74
#Sta/Elev= 30
  4529.2 1803.68  4543.0 1802.84  4613.8 1800.61  4682.3 1799.34  4719.8 1798.64
  4727.0 1798.86  4762.2 1797.40  4797.8 1796.90  4804.7 1797.12  4818.9 1796.27
  4826.1 1796.44  4847.2 1794.40  4854.4 1794.29  4861.3 1793.34  4875.5 1792.66
  4917.9 1791.70  4932.1 1791.75  4958.0 1790.91  4958.4 1790.41  4962.5 1790.41
  4962.8 1790.91  4974.6 1791.59  4988.7 1791.38  4995.6 1792.07  5031.2 1791.96
  5045.3 1792.80  5059.5 1794.64  5094.7 1794.76  5144.4 1795.94  5220.8 1796.05
#Mann=4,-1,0
  4529.2    0.12       0  4682.3    0.05       0  4958.0    0.05       0
  4962.8    0.05       0
Bank Sta=4958,4962.8
Exp/Cntr=0.3,0.1

Type RM Length L Ch R = 1,527,87,87,87
BEGIN DESCRIPTION:
Mapping XS 21a3bcfa
END DESCRIPTION:
XS GIS Cut Line= 5
      1638813.53      6883007.43      1639122.06      6883349.19
      1639183.76      6883294.61      1639368.04      6883333.00
      1639506.13      6883294.11
#Sta/Elev= 30
  4620.6 1804.11  4735.3 1798.59  4898.2 1794.67  4904.9 1794.24  4940.8 1786.61
  4955.0 1785.58  5051.3 1785.45  5051.6 1784.95  5056.1 1785.45  5067.9 1785.95
  5079.5 1788.59  5085.7 1788.59  5091.0 1787.09  5105.2 1790.34  5111.9 1789.11
  5119.4 1790.97  5126.1 1789.62  5133.7 1791.31  5140.3 1790.22  5147.9 1792.10
  5154.6 1791.48  5185.1 1793.86  5195.3 1793.81  5202.5 1792.98  5207.6 1795.15
  5226.0 1793.44  5246.4 1792.95  5252.5 1793.58  5328.1 1793.59  5495.1 1796.02
#Mann=3,-1,0
  4620.6    0.05       0  5051.3    0.05       0  5056.1    0.05       0
Bank Sta=5051.3,5056.1
Exp/Cntr=0.3,0.1

Type RM Length L Ch R = 1,440,39,39,39
BEGIN DESCRIPTION:
Mapping XS c33128af
END DESCRIPTION:
XS GIS Cut Line= 6
      1638796.91      6883073.88      1638993.90      6883337.32
      1639093.58      6883406.15      1639200.37      6883330.21
      1639345.30      6883361.26      1639511.31      6883304.46
#Sta/Elev= 30
  4653.2 1802.56  4769.9 1796.32  4890.7 1794.16  4926.2 1796.27  4947.0 1796.29
  4955.4 1795.22  4961.6 1796.06  4969.9 1794.95  4976.2 1795.74  4979.4 1794.74
  4985.9 1794.74  4990.8 1795.75  4996.9 1794.55  5005.7 1795.49  5011.8 1794.50
  5026.7 1795.56  5077.4 1795.74  5124.7 1794.96  5130.8 1793.71  5139.5 1794.26
  5145.6 1793.10  5160.4 1795.42  5181.3 1794.87  5203.2 1796.08  5239.2 1796.28
  5259.5 1795.18  5267.3 1793.03  5267.7 1792.53  5272.1 1793.03  5558.0 1796.13
#Mann=3,-1,0
  4653.2    0.05       0  5267.3    0.05       0  5272.1    0.05       0
Bank Sta=5267.3,5272.1
Exp/Cntr=0.3,0.1

Type RM Length L Ch R = 1,401,53,53,53
BEGIN DESCRIPTION:
Mapping XS a44a74d2
END DESCRIPTION:
XS GIS Cut Line= 5
      1638709.70      6883082.99      1639007.05      6883392.27
      1639066.73      6883468.23      1639126.40      6883467.14
      1639370.25      6883384.78
#Sta/Elev= 30
  4580.5 1805.55  4623.2 1803.77  4630.1 1802.60  4644.3 1802.28  4692.3 1798.74
  4830.6 1794.59  4863.7 1793.24  4884.8 1795.05  4899.0 1794.81  4913.1 1793.51
  4920.3 1791.53  4927.3 1791.35  4941.4 1789.43  4969.7 1788.13  5010.0 1787.80
  5010.3 1787.30  5014.4 1787.30  5014.8 1787.80  5041.3 1788.36  5047.6 1789.08
  5062.1 1788.88  5068.5 1790.13  5076.5 1789.48  5082.9 1790.88  5091.0 1789.90
  5205.6 1792.58  5305.3 1793.08  5331.5 1793.90  5368.2 1793.54  5423.2 1794.09
#Mann=5,-1,0
  4580.5    0.05       0  4692.3    0.12       0  4830.6    0.05       0
  5010.0    0.05       0  5014.8    0.05       0
Bank Sta=5010,5014.8
Exp/Cntr=0.3,0.1

Type RM Length L Ch R = 1,348,0,0,0
BEGIN DESCRIPTION:
Deadman 48 1.0
END DESCRIPTION:
XS GIS Cut Line= 3
      1638578.40      6883027.84      1638975.66      6883434.77
      1639139.04      6883503.42
#Sta/Elev= 30
  4443.8 1811.38  4484.0 1809.85  4505.1 1808.43  4519.3 1806.05  4526.4 1805.40
  4568.9 1805.05  4583.0 1804.26  4590.0 1804.36  4625.4 1802.26  4646.6 1801.84
  4667.7 1799.90  4710.1 1797.42  4759.7 1796.36  4773.9 1795.26  4873.7 1792.57
  4915.3 1791.67  4929.5 1790.89  4936.5 1789.43  4943.6 1789.70  4950.6 1788.59
  4997.8 1787.19  4998.2 1786.69  5002.3 1786.69  5002.6 1787.19  5089.2 1789.39
  5136.8 1791.67  5142.2 1790.97  5152.8 1790.75  5160.5 1791.39  5189.7 1791.84
#Mann=5,-1,0
  4443.8    0.05       0  4667.7    0.12       0  4873.7    0.05       0
  4997.8    0.05       0  5002.6    0.05       0
Bank Sta=4997.8,5002.6
Exp/Cntr=0.3,0.1

Chan Stop Cuts=-1