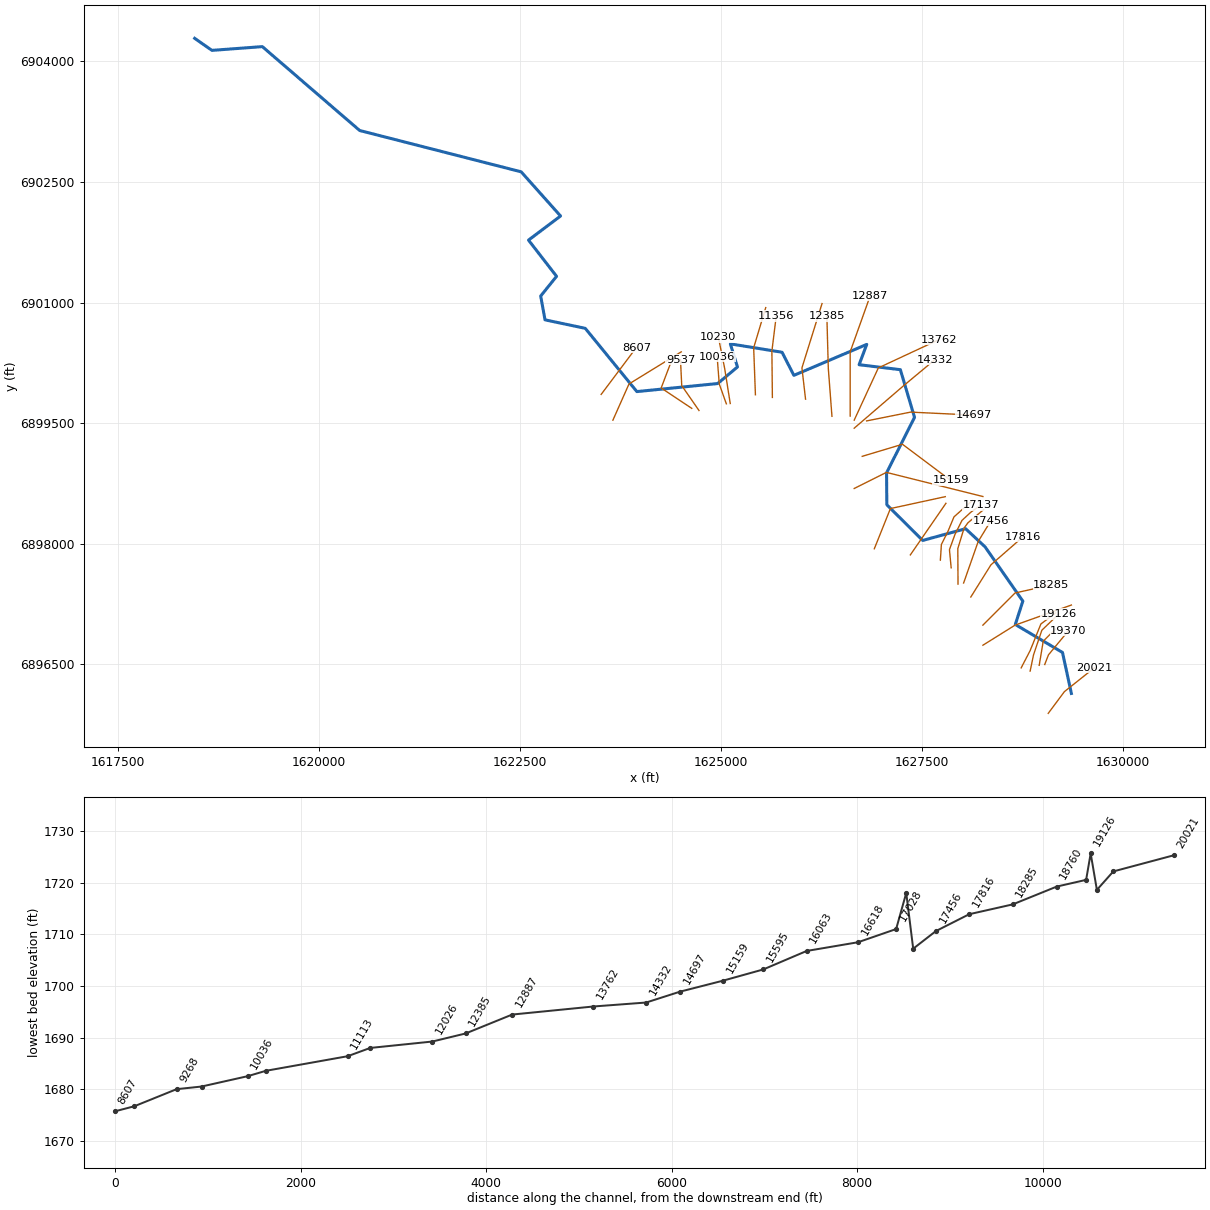
--- Deadman 49.prj (project) ---

Proj Title=Deadman 49 Base Level Engineering
Current Plan=p01
Default Exp/Contr=0.3,0.1
English Units
Geom File=g01
Flow File=f01
Plan File=p01
BEGIN DESCRIPTION:
Deadman 49
END DESCRIPTION:

--- Deadman 49.p01 (plan) ---

Plan Title=Multiple Run
Short Identifier=Multiple
Geom File=g01
Flow File=f01
Subcritical Flow
K Sum by GR= 0
Std Step Tol= 0.01
Critical Tol= 0.01
Num of Std Step Trials= 20
Max Error Tol= 0.3
Flow Tol Ratio= 0.001
Split Flow NTrial= 30
Split Flow Tol= 0.02
Split Flow Ratio= 0.02
Log Output Level= 0
Friction Slope Method= 1
Unsteady Friction Slope Method= 2
Unsteady Bridges Friction Slope Method= 1
Parabolic Critical Depth
Global Vel Dist=  1 , 1 , 1
Global Log Level= 0
CheckData=True
Encroach Param= -1, 0, 0, 0
BEGIN DESCRIPTION:
Multiple Run
END DESCRIPTION:

--- Deadman 49.f01 (steady flow) ---

Flow Title=Multiple
Number of Profiles=7
Profile Names=10-year,25-year,50-year,1pct_min,100-year,1pct_plu,500-year
River Rch & RM= Deadman 49,Reach-1,20021
     307     426     523     320     639    1275     964
River Rch & RM= Deadman 49,Reach-1,10036
     308     427     524     321     640    1276     964
River Rch & RM= Deadman 49,Reach-1,8813
     522     744     931     579    1155    2304    1800
River Rch & RM= Deadman 49,Reach-1,2372
     541     770     964     599    1196    2386    1865
Boundary for River Rch & Prof#=Deadman 49,Reach-1,1
Up Type=0
Dn Type=3
Dn Slope=0.005
Boundary for River Rch & Prof#=Deadman 49,Reach-1,2
Up Type=0
Dn Type=3
Dn Slope=0.005
Boundary for River Rch & Prof#=Deadman 49,Reach-1,3
Up Type=0
Dn Type=3
Dn Slope=0.005
Boundary for River Rch & Prof#=Deadman 49,Reach-1,4
Up Type=0
Dn Type=3
Dn Slope=0.005
Boundary for River Rch & Prof#=Deadman 49,Reach-1,5
Up Type=0
Dn Type=3
Dn Slope=0.005
Boundary for River Rch & Prof#=Deadman 49,Reach-1,6
Up Type=0
Dn Type=3
Dn Slope=0.005
Boundary for River Rch & Prof#=Deadman 49,Reach-1,7
Up Type=0
Dn Type=3
Dn Slope=0.005

--- Deadman 49.g01 (geometry) ---

Geom Title=Existing Conditions

River Reach=Deadman 49,Reach-1
Reach XY= 30
      1629355.00      6896138.00      1629244.49      6896647.81
      1628657.82      6896995.96      1628751.54      6897286.50
      1628282.14      6897961.53      1628039.84      6898187.62
      1627506.50      6898041.46      1627060.47      6898485.55
      1627057.26      6898882.07      1627404.91      6899572.60
      1627228.83      6900165.82      1626715.74      6900227.75
      1626811.09      6900480.52      1625905.08      6900095.30
      1625757.78      6900382.64      1625115.24      6900487.00
      1625203.53      6900199.50      1624957.74      6899993.34
      1623952.51      6899893.36      1623311.48      6900680.31
      1622810.82      6900785.69      1622757.06      6901082.15
      1622954.45      6901327.36      1622605.86      6901777.69
      1623004.06      6902077.51      1622514.68      6902627.24
      1620506.46      6903141.54      1619296.65      6904184.81
      1618670.22      6904138.25      1618455.00      6904288.00

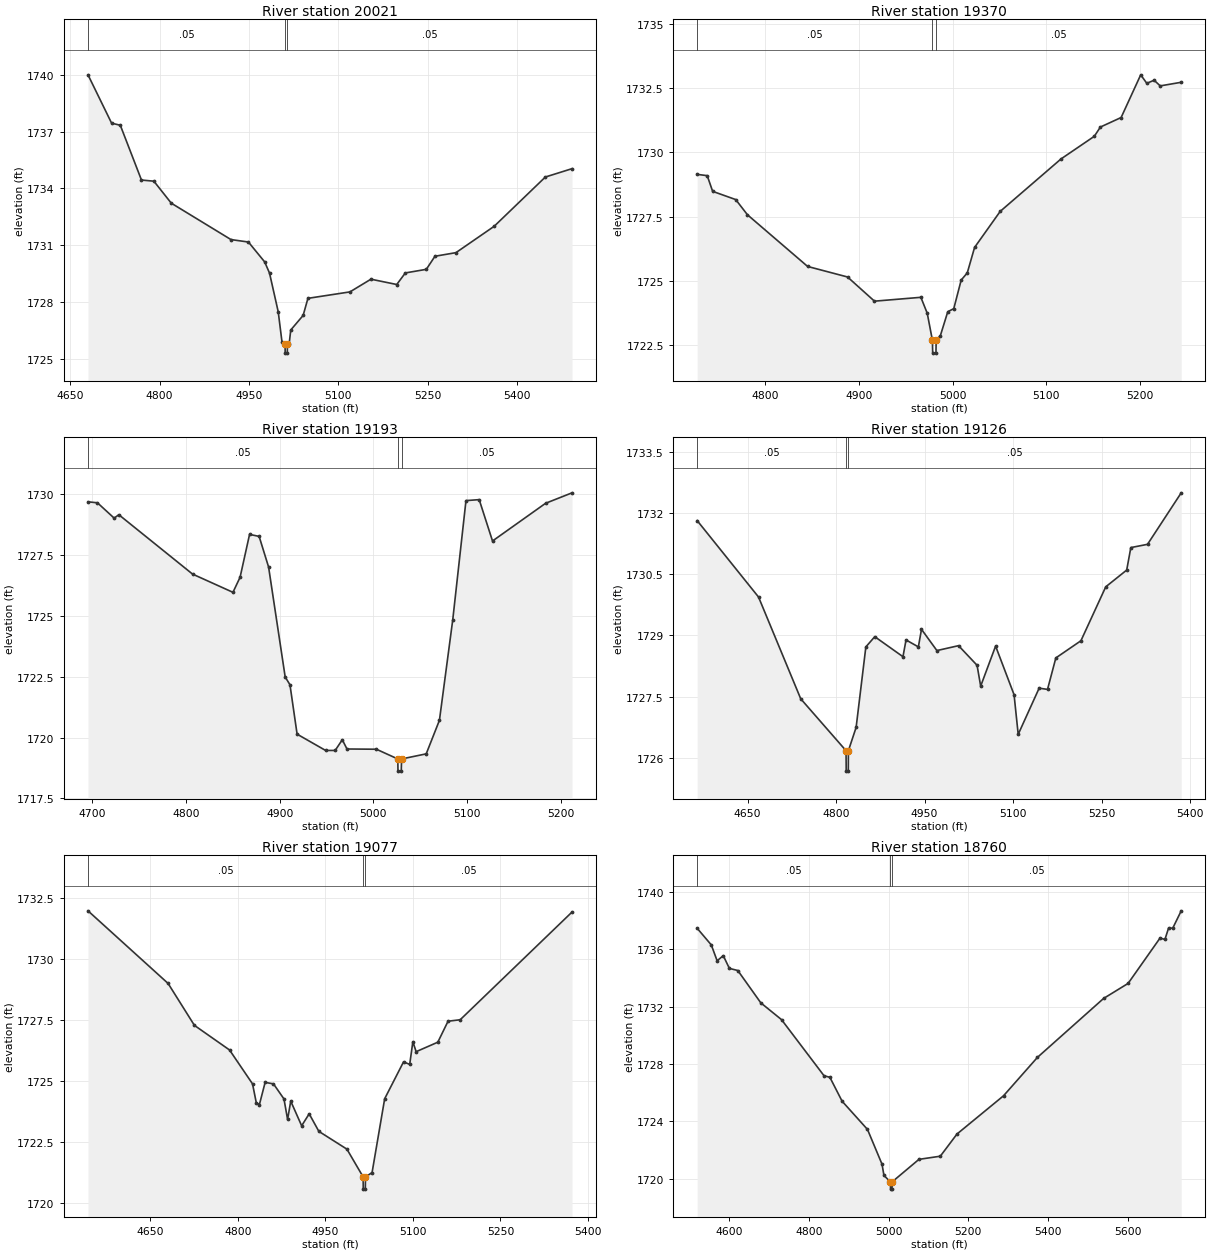
Type RM Length L Ch R = 1,20021,651,651,651
BEGIN DESCRIPTION:
Deadman 49 33.0
END DESCRIPTION:
XS GIS Cut Line= 3
      1629067.17      6895890.14      1629268.54      6896160.95
      1629640.02      6896456.05
#Sta/Elev= 30
  4680.0 1739.99  4719.6 1737.44  4734.2 1737.33  4769.7 1734.44  4790.5 1734.38
  4819.7 1733.22  4919.8 1731.30  4949.1 1731.17  4976.4 1730.12  4984.5 1729.53
  4999.1 1727.49  5005.4 1725.90  5010.5 1725.81  5010.8 1725.31  5014.3 1725.31
  5014.5 1725.81  5017.5 1725.81  5020.1 1726.53  5040.9 1727.30  5048.9 1728.20
  5119.4 1728.54  5154.6 1729.21  5197.9 1728.93  5212.3 1729.54  5247.5 1729.73
  5262.0 1730.42  5297.2 1730.61  5361.3 1732.00  5447.2 1734.60  5491.9 1735.04
#Mann=3,-1,0
  4680.0    0.05       0  5010.5    0.03       0  5014.5    0.05       0
Bank Sta=5010.5,5014.5
Exp/Cntr=0.3,0.1

Type RM Length L Ch R = 1,19370,177,177,177
BEGIN DESCRIPTION:
Mapping XS 68062ed7
END DESCRIPTION:
XS GIS Cut Line= 3
      1629023.98      6896497.98      1629069.85      6896617.65
      1629317.15      6896916.80
#Sta/Elev= 30
  4727.5 1729.14  4738.2 1729.09  4744.0 1728.48  4768.6 1728.16  4781.1 1727.57
  4845.3 1725.56  4887.9 1725.15  4916.6 1724.21  4966.1 1724.36  4972.9 1723.74
  4978.4 1722.69  4978.7 1722.19  4982.2 1722.19  4982.4 1722.69  4986.9 1722.87
  4994.8 1723.80  5001.2 1723.92  5009.1 1725.03  5015.6 1725.31  5023.4 1726.30
  5050.7 1727.70  5115.6 1729.74  5151.1 1730.62  5157.6 1730.98  5179.7 1731.35
  5200.6 1733.01  5207.1 1732.68  5214.9 1732.80  5221.4 1732.58  5243.8 1732.72
#Mann=3,-1,0
  4727.5    0.05       0  4978.4    0.05       0  4982.4    0.05       0
Bank Sta=4978.4,4982.4
Exp/Cntr=0.3,0.1

Type RM Length L Ch R = 1,19193,67,67,67
BEGIN DESCRIPTION:
Deadman 49 32.0
END DESCRIPTION:
XS GIS Cut Line= 3
      1628955.00      6896488.03      1629005.00      6896788.00
      1629154.97      6896937.97
#Sta/Elev= 30
  4695.6 1729.69  4705.7 1729.65  4723.5 1729.02  4728.5 1729.16  4807.1 1726.72
  4850.2 1725.97  4857.8 1726.59  4867.9 1728.35  4878.1 1728.27  4888.2 1727.01
  4905.9 1722.49  4911.0 1722.17  4918.6 1720.14  4949.0 1719.47  4959.2 1719.47
  4966.8 1719.91  4971.8 1719.53  5003.2 1719.52  5026.0 1719.12  5026.2 1718.62
  5029.7 1718.62  5030.0 1719.12  5056.3 1719.33  5070.4 1720.71  5084.6 1724.84
  5098.7 1729.74  5112.8 1729.78  5127.0 1728.08  5183.6 1729.63  5211.8 1730.06
#Mann=3,-1,0
  4695.6    0.05       0  5026.0    0.03       0  5030.0    0.05       0
Bank Sta=5026,5030
Exp/Cntr=0.3,0.1

Type RM Length L Ch R = 1,19126,49,49,49
BEGIN DESCRIPTION:
Mapping XS 2e5a50fb
END DESCRIPTION:
XS GIS Cut Line= 5
      1628842.51      6896416.22      1628884.39      6896617.65
      1628910.32      6896695.43      1628988.09      6896924.76
      1629197.47      6897126.16
#Sta/Elev= 30
  4564.6 1731.81  4668.6 1729.94  4740.1 1727.45  4816.9 1726.18  4817.2 1725.68
  4820.7 1725.68  4820.9 1726.18  4834.0 1726.75  4850.5 1728.72  4865.6 1728.97
  4913.4 1728.48  4918.6 1728.89  4939.5 1728.72  4944.8 1729.15  4970.9 1728.63
  5007.6 1728.75  5039.0 1728.27  5045.1 1727.76  5070.4 1728.74  5101.7 1727.55
  5108.7 1726.58  5144.2 1727.71  5158.4 1727.68  5172.5 1728.45  5215.0 1728.87
  5257.1 1730.19  5292.6 1730.60  5299.6 1731.15  5327.9 1731.23  5385.0 1732.49
#Mann=3,-1,0
  4564.6    0.05       0  4816.9    0.03       0  4820.9    0.05       0
Bank Sta=4816.9,4820.9
Exp/Cntr=0.3,0.1

Type RM Length L Ch R = 1,19077,317,317,317
BEGIN DESCRIPTION:
Mapping XS 34cf925d
END DESCRIPTION:
XS GIS Cut Line= 4
      1628730.82      6896456.08      1628842.51      6896671.50
      1628976.12      6897002.53      1629160.81      6897139.56
#Sta/Elev= 30
  4543.2 1731.98  4680.5 1729.00  4725.6 1727.28  4785.8 1726.27  4825.2 1724.88
  4831.6 1724.11  4837.0 1724.03  4846.8 1724.94  4861.1 1724.88  4879.1 1724.26
  4885.3 1723.42  4890.7 1724.17  4909.4 1723.16  4922.3 1723.65  4938.9 1722.93
  4987.0 1722.20  5014.8 1721.06  5015.0 1720.56  5018.5 1720.56  5018.8 1721.06
  5030.1 1721.24  5051.7 1724.27  5084.0 1725.78  5094.6 1725.68  5100.0 1726.61
  5105.6 1726.20  5142.8 1726.59  5160.3 1727.45  5181.1 1727.51  5372.8 1731.93
#Mann=3,-1,0
  4543.2    0.05       0  5014.8    0.03       0  5018.8    0.05       0
Bank Sta=5014.8,5018.8
Exp/Cntr=0.3,0.1

Type RM Length L Ch R = 1,18760,475,475,475
BEGIN DESCRIPTION:
Deadman 49 31.0
END DESCRIPTION:
XS GIS Cut Line= 3
      1628254.99      6896738.00      1628655.00      6896988.00
      1629354.99      6897238.00
#Sta/Elev= 30
  4519.7 1737.48  4555.1 1736.32  4569.8 1735.21  4585.2 1735.57  4600.5 1734.68
  4621.7 1734.53  4679.5 1732.27  4731.4 1731.10  4838.1 1727.18  4852.8 1727.07
  4883.5 1725.40  4947.2 1723.43  4983.7 1721.00  4988.5 1720.22  5004.8 1719.76
  5005.1 1719.26  5008.6 1719.26  5008.8 1719.76  5076.4 1721.34  5130.0 1721.56
  5171.9 1723.11  5288.7 1725.78  5373.7 1728.46  5539.9 1732.58  5601.4 1733.63
  5681.6 1736.80  5693.8 1736.70  5702.9 1737.49  5713.5 1737.49  5734.7 1738.70
#Mann=3,-1,0
  4519.7    0.05       0  5004.8    0.05       0  5008.8    0.05       0
Bank Sta=5004.8,5008.8
Exp/Cntr=0.3,0.1

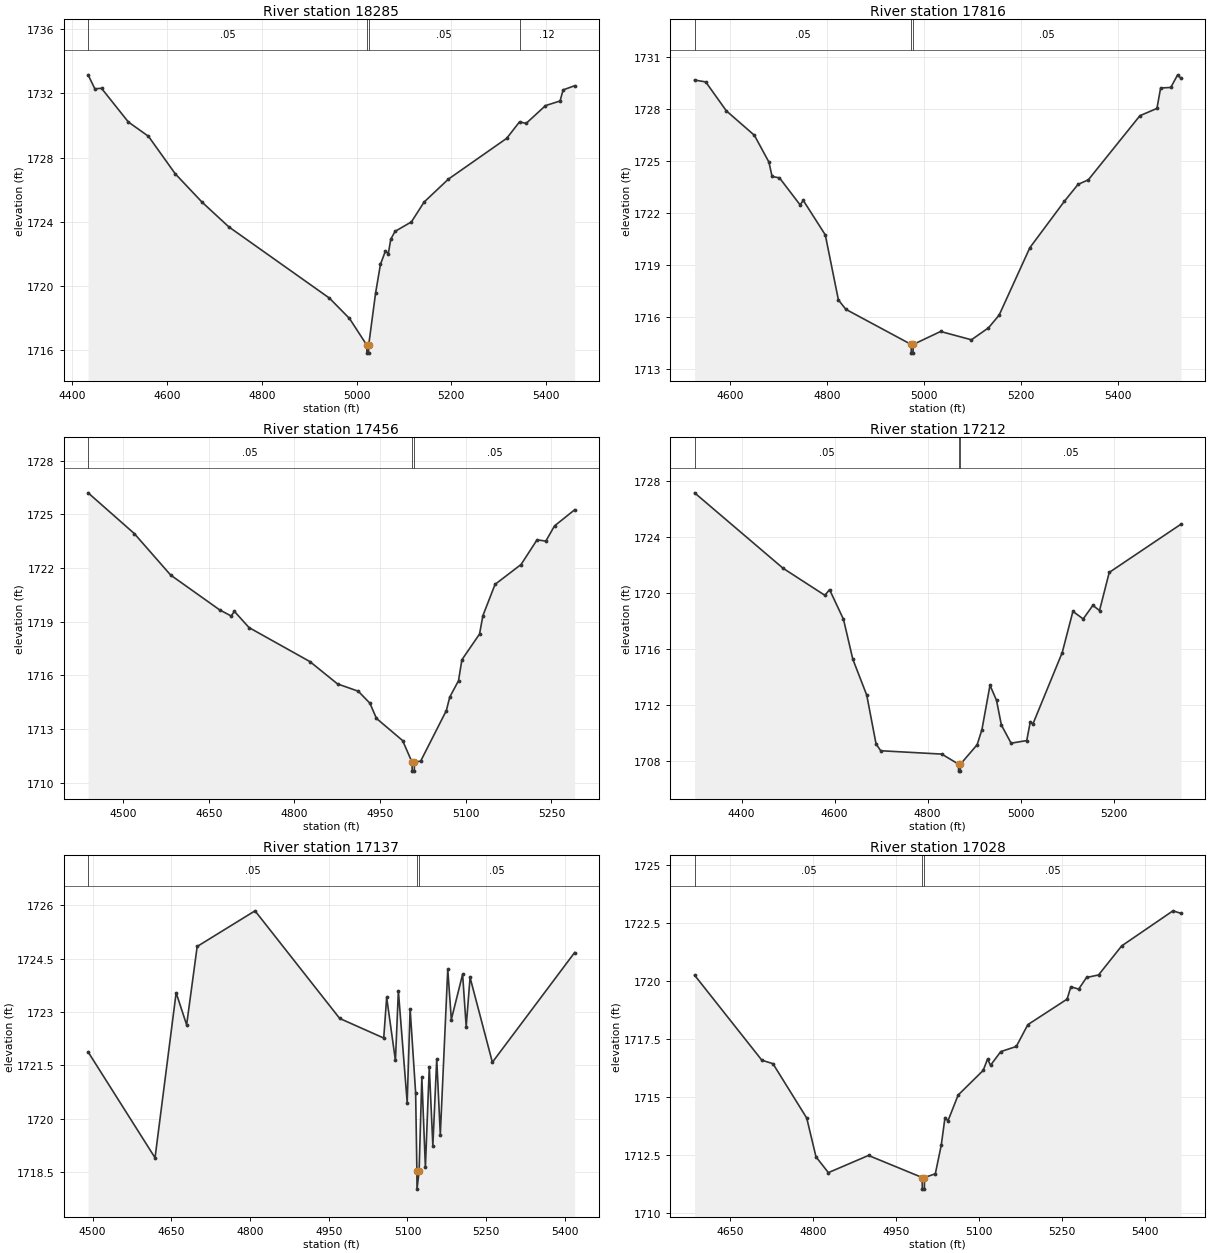
Type RM Length L Ch R = 1,18285,469,469,469
BEGIN DESCRIPTION:
Deadman 49 30.0
END DESCRIPTION:
XS GIS Cut Line= 3
      1628254.97      6896987.97      1628655.00      6897388.00
      1629105.00      6897488.00
#Sta/Elev= 30
  4433.5 1733.16  4447.7 1732.29  4461.8 1732.32  4518.4 1730.22  4560.8 1729.33
  4617.4 1726.99  4674.0 1725.22  4730.5 1723.68  4942.7 1719.24  4985.1 1717.97
  5021.6 1716.31  5021.8 1715.81  5025.3 1715.81  5025.6 1716.31  5040.2 1719.56
  5050.4 1721.34  5060.7 1722.16  5067.1 1722.02  5072.2 1722.91  5081.2 1723.40
  5115.7 1723.99  5142.6 1725.23  5193.9 1726.66  5316.8 1729.20  5344.0 1730.23
  5357.8 1730.13  5398.7 1731.24  5429.5 1731.53  5435.9 1732.22  5460.2 1732.48
#Mann=4,-1,0
  4433.5    0.05       0  5021.6    0.05       0  5025.6    0.05       0
  5344.0    0.12       0
Bank Sta=5021.6,5025.6
Exp/Cntr=0.3,0.1

Type RM Length L Ch R = 1,17816,360,360,360
BEGIN DESCRIPTION:
Deadman 49 29.0
END DESCRIPTION:
XS GIS Cut Line= 3
      1628104.99      6897337.98      1628355.00      6897738.00
      1628754.98      6898087.98
#Sta/Elev= 30
  4527.3 1729.68  4550.3 1729.57  4592.8 1727.90  4650.6 1726.49  4680.6 1724.94
  4687.1 1724.11  4702.4 1724.03  4744.9 1722.47  4751.4 1722.73  4796.8 1720.74
  4823.9 1716.98  4839.2 1716.44  4974.0 1714.41  4974.2 1713.91  4977.8 1713.91
  4978.1 1714.41  5034.6 1715.16  5098.2 1714.68  5133.3 1715.37  5155.2 1716.10
  5218.7 1720.00  5289.9 1722.68  5317.9 1723.65  5339.3 1723.92  5445.6 1727.62
  5480.7 1728.04  5488.3 1729.22  5509.2 1729.25  5523.4 1729.98  5530.5 1729.77
#Mann=3,-1,0
  4527.3    0.05       0  4974.0    0.05       0  4978.1    0.05       0
Bank Sta=4974,4978.1
Exp/Cntr=0.3,0.1

Type RM Length L Ch R = 1,17456,244,244,244
BEGIN DESCRIPTION:
Deadman 49 28.0
END DESCRIPTION:
XS GIS Cut Line= 3
      1628015.07      6897511.62      1628196.79      6898029.10
      1628355.02      6898288.03
#Sta/Elev= 30
  4438.7 1726.21  4519.6 1723.93  4583.2 1721.61  4669.1 1719.66  4689.2 1719.32
  4694.8 1719.58  4720.5 1718.67  4827.0 1716.77  4875.4 1715.52  4911.8 1715.11
  4932.1 1714.44  4943.6 1713.59  4989.4 1712.35  5005.9 1711.14  5006.2 1710.64
  5009.8 1710.64  5010.1 1711.14  5021.0 1711.20  5066.0 1714.03  5071.9 1714.78
  5087.3 1715.70  5093.2 1716.87  5124.1 1718.31  5130.0 1719.34  5151.3 1721.09
  5196.8 1722.20  5224.8 1723.58  5240.2 1723.51  5255.4 1724.36  5290.6 1725.26
#Mann=3,-1,0
  4438.7    0.05       0  5005.9    0.05       0  5010.1    0.05       0
Bank Sta=5005.9,5010.1
Exp/Cntr=0.3,0.1

Type RM Length L Ch R = 1,17212,75,75,75
BEGIN DESCRIPTION:
Mapping XS ff517520
END DESCRIPTION:
XS GIS Cut Line= 5
      1627945.63      6897497.78      1627943.14      6897939.79
      1628021.26      6898195.87      1628069.01      6898260.98
      1628264.30      6898425.89
#Sta/Elev= 30
  4298.8 1727.17  4489.0 1721.77  4579.0 1719.83  4589.0 1720.24  4619.0 1718.11
  4639.0 1715.26  4669.0 1712.68  4689.0 1709.19  4699.0 1708.70  4830.3 1708.46
  4866.3 1707.74  4866.5 1707.24  4870.2 1707.24  4870.5 1707.74  4906.4 1709.13
  4916.7 1710.22  4934.0 1713.39  4948.0 1712.31  4958.5 1710.54  4979.4 1709.24
  5013.0 1709.43  5020.4 1710.73  5026.6 1710.64  5089.3 1715.73  5112.3 1718.68
  5134.4 1718.14  5155.2 1719.11  5169.5 1718.74  5190.4 1721.47  5344.9 1724.93
#Mann=3,-1,0
  4298.8    0.05       0  4866.3    0.05       0  4870.5    0.05       0
Bank Sta=4866.3,4870.5
Exp/Cntr=0.3,0.1

Type RM Length L Ch R = 1,17137,109,109,109
BEGIN DESCRIPTION:
Mapping XS 051ec41f
END DESCRIPTION:
XS GIS Cut Line= 6
      1627860.67      6897701.12      1627838.97      6897926.77
      1627908.42      6898117.75      1627995.22      6898291.36
      1628108.07      6898395.52      1628229.57      6898482.31
#Sta/Elev= 30
  4491.6 1721.88  4619.1 1718.91  4659.3 1723.54  4679.3 1722.64  4699.4 1724.84
  4809.6 1725.84  4970.9 1722.82  5054.8 1722.27  5060.4 1723.41  5077.1 1721.64
  5082.7 1723.59  5099.5 1720.46  5105.1 1723.09  5115.6 1720.73  5118.0 1718.53
  5118.2 1718.03  5122.2 1718.53  5127.4 1721.17  5134.2 1718.64  5141.6 1721.46
  5148.4 1719.25  5155.8 1721.68  5162.6 1719.56  5176.8 1724.20  5183.6 1722.79
  5205.1 1724.06  5211.9 1722.59  5219.3 1723.97  5261.8 1721.59  5418.5 1724.67
#Mann=3,-1,0
  4491.6    0.05       0  5118.0    0.03       0  5122.2    0.05       0
Bank Sta=5118,5122.2
Exp/Cntr=0.3,0.1

Type RM Length L Ch R = 1,17028,410,410,410
BEGIN DESCRIPTION:
Mapping XS ef15e7a4
END DESCRIPTION:
XS GIS Cut Line= 5
      1627726.12      6897796.54      1627739.15      6897991.88
      1627821.61      6898156.81      1627895.40      6898334.76
      1628125.45      6898538.77
#Sta/Elev= 30
  4585.7 1720.25  4707.4 1716.59  4727.5 1716.44  4788.6 1714.10  4805.4 1712.43
  4827.8 1711.75  4900.4 1712.49  4997.5 1711.54  4997.8 1711.04  5001.5 1711.04
  5001.7 1711.54  5021.3 1711.70  5032.1 1712.94  5038.8 1714.12  5044.2 1713.98
  5062.6 1715.09  5107.9 1716.15  5115.8 1716.64  5121.2 1716.37  5139.7 1716.96
  5167.8 1717.18  5188.7 1718.12  5259.8 1719.22  5266.5 1719.75  5280.7 1719.65
  5294.9 1720.15  5316.7 1720.26  5358.5 1721.51  5451.3 1723.02  5466.0 1722.91
#Mann=3,-1,0
  4585.7    0.05       0  4997.5    0.05       0  5001.7    0.05       0
Bank Sta=4997.5,5001.7
Exp/Cntr=0.3,0.1

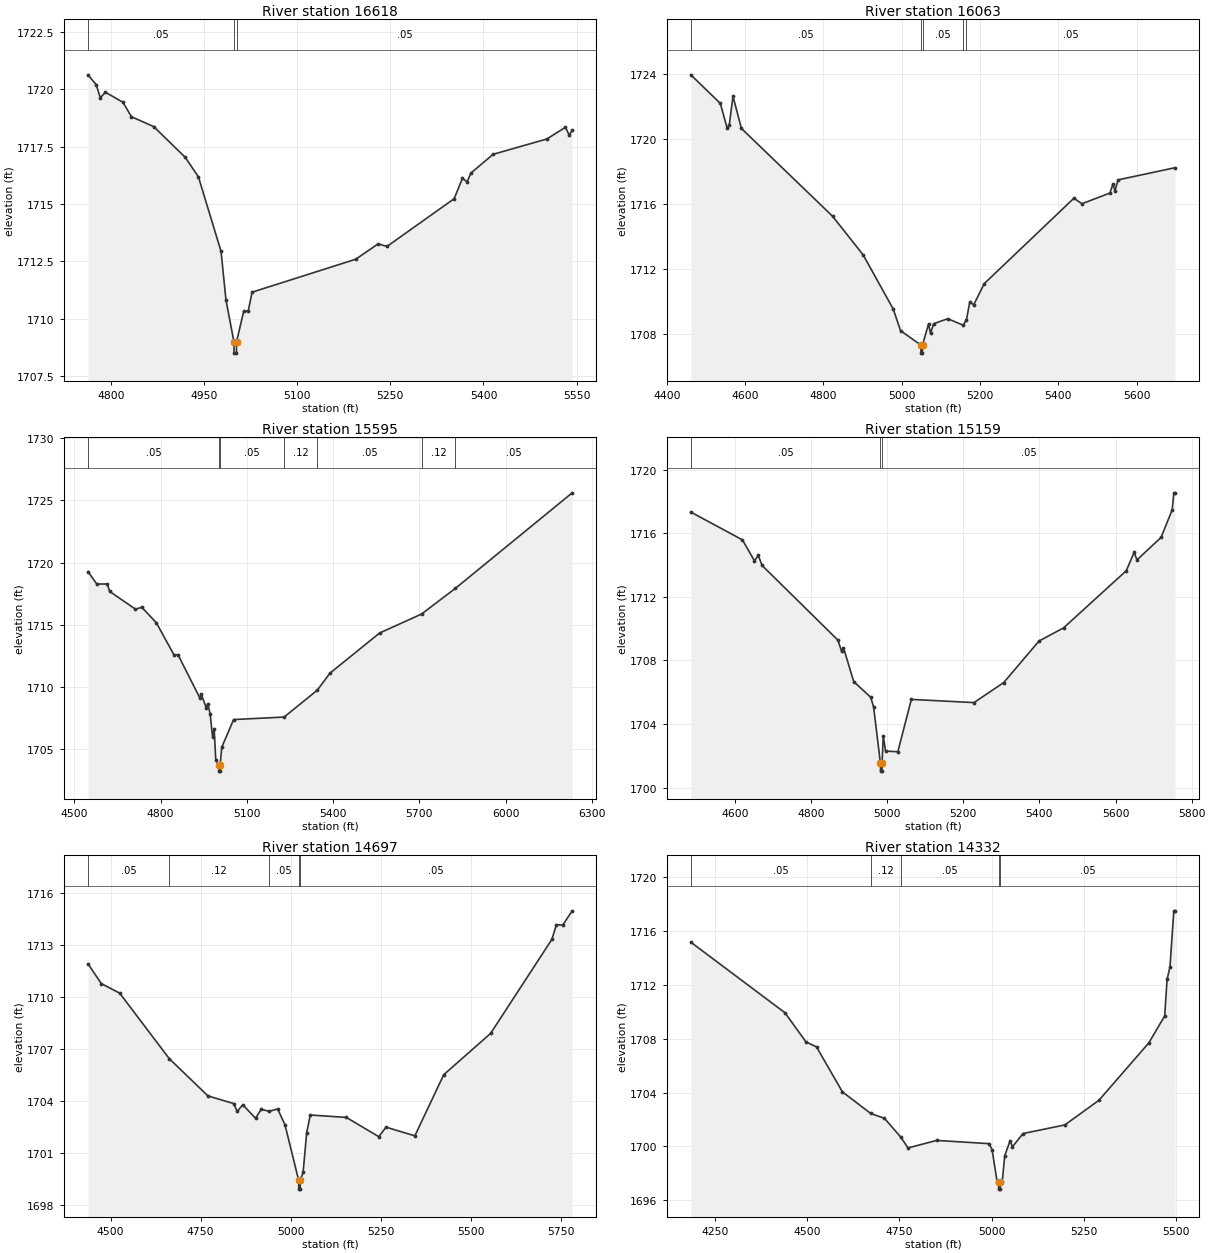
Type RM Length L Ch R = 1,16618,555,555,555
BEGIN DESCRIPTION:
Mapping XS 466e2987
END DESCRIPTION:
XS GIS Cut Line= 2
      1627352.85      6897861.66      1627795.20      6898503.49
#Sta/Elev= 30
  4763.4 1720.64  4776.6 1720.21  4783.2 1719.64  4791.5 1719.88  4819.7 1719.44
  4833.4 1718.81  4869.2 1718.38  4919.9 1717.04  4941.1 1716.19  4977.6 1712.93
  4985.5 1710.81  4998.3 1708.99  4998.6 1708.49  5002.3 1708.49  5002.6 1708.99
  5014.0 1710.31  5021.4 1710.33  5027.5 1711.15  5194.5 1712.59  5230.4 1713.26
  5244.8 1713.15  5352.8 1715.23  5366.2 1716.12  5373.7 1715.97  5379.8 1716.35
  5415.6 1717.17  5502.2 1717.84  5532.0 1718.35  5538.0 1718.01  5542.9 1718.21
#Mann=3,-1,0
  4763.4    0.05       0  4998.3    0.05       0  5002.6    0.05       0
Bank Sta=4998.3,5002.6
Exp/Cntr=0.3,0.1

Type RM Length L Ch R = 1,16063,468,468,468
BEGIN DESCRIPTION:
Deadman 49 27.0
END DESCRIPTION:
XS GIS Cut Line= 3
      1626905.01      6897938.03      1627105.00      6898438.00
      1627787.32      6898586.11
#Sta/Elev= 30
  4461.4 1723.94  4536.8 1722.18  4554.3 1720.65  4559.6 1720.84  4569.1 1722.62
  4590.6 1720.64  4823.5 1715.23  4901.6 1712.85  4978.3 1709.52  4997.2 1708.18
  5048.9 1707.30  5049.2 1706.80  5052.9 1706.80  5053.2 1707.30  5068.5 1708.59
  5073.6 1708.03  5081.7 1708.61  5117.7 1708.92  5157.0 1708.52  5165.5 1708.85
  5173.8 1709.94  5184.1 1709.78  5210.8 1711.08  5439.9 1716.34  5460.4 1716.00
  5532.0 1716.66  5539.6 1717.23  5544.7 1716.79  5552.5 1717.47  5698.1 1718.22
#Mann=5,-1,0
  4461.4    0.05       0  5048.9    0.03       0  5053.2    0.05       0
  5157.0    0.12       0  5165.5    0.05       0
Bank Sta=5048.9,5053.2
Exp/Cntr=0.3,0.1

Type RM Length L Ch R = 1,15595,436,436,436
BEGIN DESCRIPTION:
Deadman 49 26.0
END DESCRIPTION:
XS GIS Cut Line= 3
      1626655.02      6898688.01      1627055.00      6898888.00
      1628254.98      6898588.01
#Sta/Elev= 30
  4547.8 1719.27  4578.5 1718.27  4614.9 1718.28  4623.2 1717.68  4712.7 1716.25
  4735.0 1716.40  4785.4 1715.16  4846.9 1712.57  4860.8 1712.59  4936.3 1709.13
  4941.9 1709.41  4958.7 1708.33  4964.2 1708.64  4972.6 1707.85  4981.0 1705.99
  4986.6 1706.62  4992.2 1704.12  5003.1 1703.72  5003.4 1703.22  5007.2 1703.22
  5007.4 1703.72  5013.0 1705.14  5054.3 1707.37  5230.0 1707.57  5345.6 1709.74
  5389.3 1711.10  5561.9 1714.33  5708.1 1715.86  5825.4 1717.92  6231.9 1725.61
#Mann=7,-1,0
  4547.8    0.05       0  5003.1    0.05       0  5007.4    0.05       0
  5230.0    0.12       0  5345.6    0.05       0  5708.1    0.12       0
  5825.4    0.05       0
Bank Sta=5003.1,5007.4
Exp/Cntr=0.3,0.1

Type RM Length L Ch R = 1,15159,462,462,462
BEGIN DESCRIPTION:
Deadman 49 25.0
END DESCRIPTION:
XS GIS Cut Line= 3
      1626755.01      6899088.00      1627255.00      6899238.00
      1627854.99      6898788.00
#Sta/Elev= 30
  4484.3 1717.33  4620.0 1715.58  4651.3 1714.27  4661.8 1714.60  4671.3 1713.98
  4870.6 1709.28  4880.2 1708.60  4885.4 1708.80  4912.3 1706.67  4956.7 1705.69
  4964.5 1705.08  4982.4 1701.54  4982.7 1701.04  4986.5 1701.04  4986.8 1701.54
  4989.8 1703.27  4995.9 1702.30  5028.2 1702.26  5063.6 1705.55  5228.2 1705.35
  5306.3 1706.61  5399.0 1709.22  5463.6 1710.05  5628.2 1713.64  5649.0 1714.80
  5656.3 1714.32  5719.8 1715.74  5749.0 1717.48  5753.2 1718.54  5756.3 1718.54
#Mann=3,-1,0
  4484.3    0.05       0  4982.4    0.05       0  4986.8    0.05       0
Bank Sta=4982.4,4986.8
Exp/Cntr=0.3,0.1

Type RM Length L Ch R = 1,14697,365,365,365
BEGIN DESCRIPTION:
Deadman 49 24.0
END DESCRIPTION:
XS GIS Cut Line= 3
      1626808.83      6899528.50      1627355.00      6899638.00
      1628141.28      6899600.81
#Sta/Elev= 30
  4437.2 1711.90  4474.1 1710.76  4525.1 1710.21  4662.6 1706.44  4770.1 1704.29
  4841.3 1703.85  4851.5 1703.40  4866.9 1703.78  4902.4 1703.00  4917.8 1703.52
  4940.4 1703.40  4963.6 1703.54  4984.0 1702.63  5022.1 1699.42  5022.4 1698.92
  5026.2 1698.92  5026.5 1699.42  5034.3 1699.88  5044.3 1702.17  5054.3 1703.19
  5154.4 1703.05  5244.5 1701.94  5264.5 1702.49  5344.6 1701.99  5424.7 1705.51
  5554.9 1707.89  5725.1 1713.31  5737.6 1714.15  5755.1 1714.13  5781.4 1714.95
#Mann=5,-1,0
  4437.2    0.05       0  4662.6    0.12       0  4940.4    0.05       0
  5022.1    0.03       0  5026.5    0.05       0
Bank Sta=5022.1,5026.5
Exp/Cntr=0.3,0.1

Type RM Length L Ch R = 1,14332,570,570,570
BEGIN DESCRIPTION:
Deadman 49 23.0
END DESCRIPTION:
XS GIS Cut Line= 3
      1626654.98      6899437.98      1627271.15      6899968.24
      1627655.00      6900288.00
#Sta/Elev= 30
  4184.5 1715.17  4439.6 1709.93  4496.7 1707.76  4525.2 1707.39  4595.4 1704.05
  4672.3 1702.44  4709.5 1702.08  4753.8 1700.68  4773.2 1699.88  4851.1 1700.44
  4992.6 1700.20  5001.1 1699.76  5014.7 1697.38  5018.7 1697.32  5019.1 1696.82
  5023.4 1696.82  5023.8 1697.32  5028.5 1697.33  5035.5 1699.31  5049.9 1700.41
  5056.4 1699.97  5085.0 1700.95  5198.3 1701.59  5290.7 1703.42  5426.1 1707.69
  5469.0 1709.69  5475.5 1712.40  5483.3 1713.32  5493.8 1717.50  5497.0 1717.50
#Mann=5,-1,0
  4184.5    0.05       0  4672.3    0.12       0  4753.8    0.05       0
  5018.7    0.03       0  5023.8    0.05       0
Bank Sta=5018.7,5023.8
Exp/Cntr=0.3,0.1

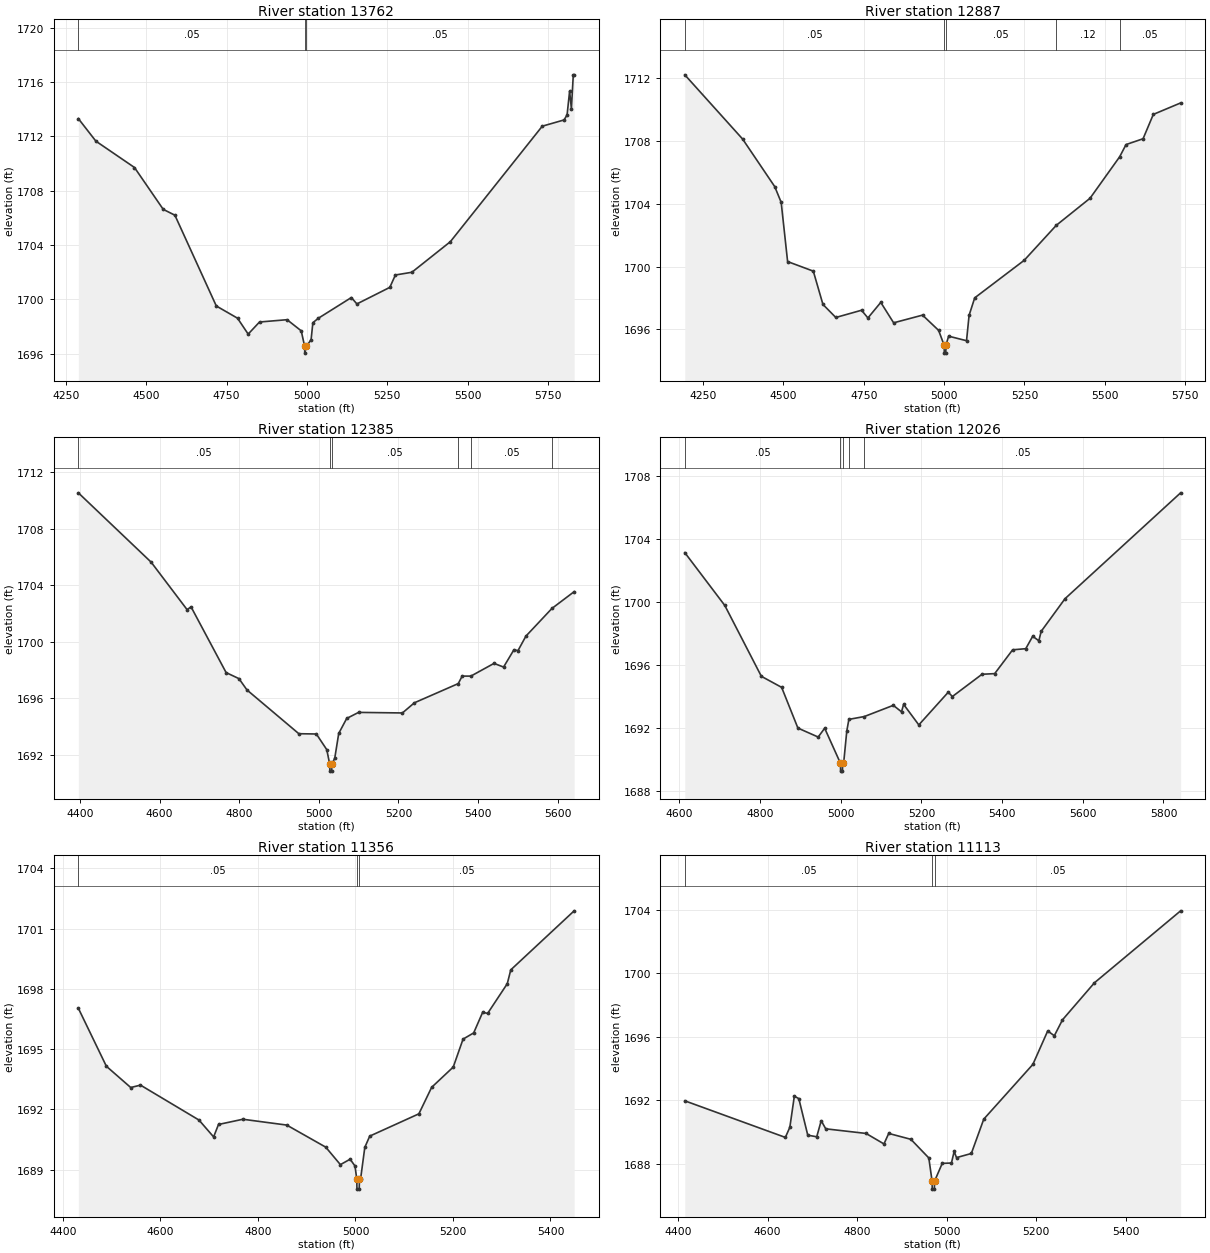
Type RM Length L Ch R = 1,13762,875,875,875
BEGIN DESCRIPTION:
Deadman 49 22.0
END DESCRIPTION:
XS GIS Cut Line= 3
      1626655.00      6899538.00      1626955.00      6900188.00
      1627704.97      6900537.98
#Sta/Elev= 30
  4288.2 1713.31  4342.8 1711.65  4463.0 1709.71  4552.5 1706.63  4588.8 1706.20
  4717.7 1699.52  4783.8 1698.62  4816.9 1697.45  4852.2 1698.34  4938.0 1698.51
  4982.1 1697.69  4992.7 1696.55  4993.1 1696.05  4998.0 1696.55  5012.8 1697.04
  5018.3 1698.29  5035.6 1698.62  5138.1 1700.14  5155.4 1699.67  5257.9 1700.89
  5275.2 1701.80  5326.5 1702.00  5446.3 1704.25  5732.4 1712.75  5800.2 1713.21
  5809.7 1713.58  5817.5 1715.32  5823.1 1714.05  5829.0 1716.53  5831.7 1716.53
#Mann=3,-1,0
  4288.2    0.05       0  4992.7    0.03       0  4998.0    0.05       0
Bank Sta=4992.7,4998
Exp/Cntr=0.3,0.1

Type RM Length L Ch R = 1,12887,502,502,502
BEGIN DESCRIPTION:
Deadman 49 21.0
END DESCRIPTION:
XS GIS Cut Line= 3
      1626605.00      6899588.05      1626605.00      6900388.00
      1626855.02      6901088.04
#Sta/Elev= 30
  4192.9 1712.21  4372.9 1708.12  4472.9 1705.09  4492.9 1704.09  4512.9 1700.32
  4592.9 1699.71  4622.9 1697.59  4662.9 1696.76  4742.9 1697.22  4762.9 1696.73
  4802.9 1697.72  4842.9 1696.42  4932.9 1696.91  4982.9 1695.94  5000.2 1694.99
  5000.7 1694.49  5005.2 1694.49  5005.6 1694.99  5014.1 1695.57  5069.8 1695.28
  5077.8 1696.90  5095.3 1698.01  5249.3 1700.40  5349.3 1702.63  5454.2 1704.35
  5546.4 1706.99  5566.3 1707.77  5619.3 1708.14  5651.2 1709.69  5736.2 1710.42
#Mann=5,-1,0
  4192.9    0.05       0  5000.2    0.03       0  5005.6    0.05       0
  5349.3    0.12       0  5546.4    0.05       0
Bank Sta=5000.2,5005.6
Exp/Cntr=0.3,0.1

Type RM Length L Ch R = 1,12385,359,359,359
BEGIN DESCRIPTION:
Deadman 49 20.0
END DESCRIPTION:
XS GIS Cut Line= 3
      1626378.26      6899585.65      1626333.09      6900181.84
      1626315.03      6900829.19
#Sta/Elev= 30
  4396.0 1710.54  4578.9 1705.63  4669.1 1702.27  4679.2 1702.46  4767.2 1697.81
  4799.5 1697.38  4819.6 1696.58  4949.9 1693.48  4993.9 1693.46  5020.1 1692.35
  5027.4 1691.33  5027.8 1690.83  5032.4 1690.83  5032.8 1691.33  5040.1 1691.74
  5050.1 1693.50  5070.1 1694.56  5099.9 1694.99  5210.1 1694.95  5240.2 1695.67
  5350.4 1697.03  5360.2 1697.56  5382.1 1697.56  5440.2 1698.46  5464.2 1698.20
  5490.3 1699.43  5500.3 1699.36  5520.3 1700.39  5585.6 1702.35  5641.5 1703.54
#Mann=6,-1,0
  4396.0    0.05       0  5027.4    0.03       0  5032.8    0.05       0
  5350.4    0.12       0  5382.1    0.05       0  5585.6    0.12       0
Bank Sta=5027.4,5032.8
Exp/Cntr=0.3,0.1

Type RM Length L Ch R = 1,12026,670,670,670
BEGIN DESCRIPTION:
Deadman 49 19.0
END DESCRIPTION:
XS GIS Cut Line= 3
      1626050.07      6899799.47      1626005.00      6900188.00
      1626255.00      6900988.01
#Sta/Elev= 30
  4613.3 1703.12  4712.5 1699.77  4803.1 1695.28  4853.4 1694.58  4893.7 1692.00
  4944.0 1691.43  4960.1 1691.99  4999.2 1689.77  4999.6 1689.27  5004.2 1689.27
  5004.6 1689.77  5007.1 1689.77  5014.9 1691.81  5020.1 1692.55  5058.4 1692.73
  5130.2 1693.44  5150.6 1693.03  5155.8 1693.50  5193.5 1692.20  5266.4 1694.27
  5276.8 1694.00  5350.2 1695.41  5381.6 1695.45  5426.1 1696.96  5458.6 1697.03
  5475.9 1697.82  5491.1 1697.53  5496.9 1698.13  5556.0 1700.20  5842.6 1706.91
#Mann=5,-1,0
  4613.3    0.05       0  4999.2    0.03       0  5004.6    0.05       0
  5020.1    0.12       0  5058.4    0.05       0
Bank Sta=4999.2,5004.6
Exp/Cntr=0.3,0.1

Type RM Length L Ch R = 1,11356,243,243,243
BEGIN DESCRIPTION:
Mapping XS 174313d9
END DESCRIPTION:
XS GIS Cut Line= 3
      1625637.59      6899820.49      1625631.57      6900395.61
      1625685.63      6900834.14
#Sta/Elev= 30
  4431.6 1697.04  4489.1 1694.15  4539.1 1693.09  4559.1 1693.21  4679.1 1691.47
  4709.1 1690.63  4719.1 1691.25  4769.1 1691.51  4859.1 1691.22  4939.1 1690.12
  4969.1 1689.25  4989.1 1689.52  4999.1 1689.18  5002.7 1688.53  5003.1 1688.03
  5007.7 1688.03  5008.2 1688.53  5010.5 1688.53  5019.2 1690.11  5029.3 1690.67
  5130.1 1691.78  5156.3 1693.10  5200.6 1694.11  5220.7 1695.50  5242.5 1695.81
  5261.0 1696.84  5271.1 1696.78  5311.4 1698.26  5318.6 1698.95  5448.6 1701.89
#Mann=3,-1,0
  4431.6    0.05       0  5002.7    0.03       0  5008.2    0.05       0
Bank Sta=5002.7,5008.2
Exp/Cntr=0.3,0.1

Type RM Length L Ch R = 1,11113,883,883,883
BEGIN DESCRIPTION:
Deadman 49 18.0
END DESCRIPTION:
XS GIS Cut Line= 3
      1625426.83      6899853.66      1625405.00      6900438.00
      1625555.01      6900938.04
#Sta/Elev= 30
  4415.3 1691.98  4639.8 1689.68  4649.8 1690.32  4659.8 1692.27  4669.8 1692.12
  4689.8 1689.82  4709.8 1689.72  4719.8 1690.73  4729.9 1690.22  4819.9 1689.93
  4859.9 1689.27  4870.5 1689.93  4920.0 1689.56  4960.0 1688.39  4967.3 1686.93
  4967.7 1686.43  4972.4 1686.43  4972.8 1686.93  4990.0 1688.05  5010.5 1688.07
  5016.6 1688.80  5021.8 1688.41  5054.9 1688.67  5082.7 1690.83  5192.3 1694.27
  5225.4 1696.37  5240.2 1696.07  5258.4 1697.07  5329.8 1699.40  5522.1 1703.92
#Mann=3,-1,0
  4415.3    0.05       0  4967.3    0.03       0  4972.8    0.05       0
Bank Sta=4967.3,4972.8
Exp/Cntr=0.3,0.1

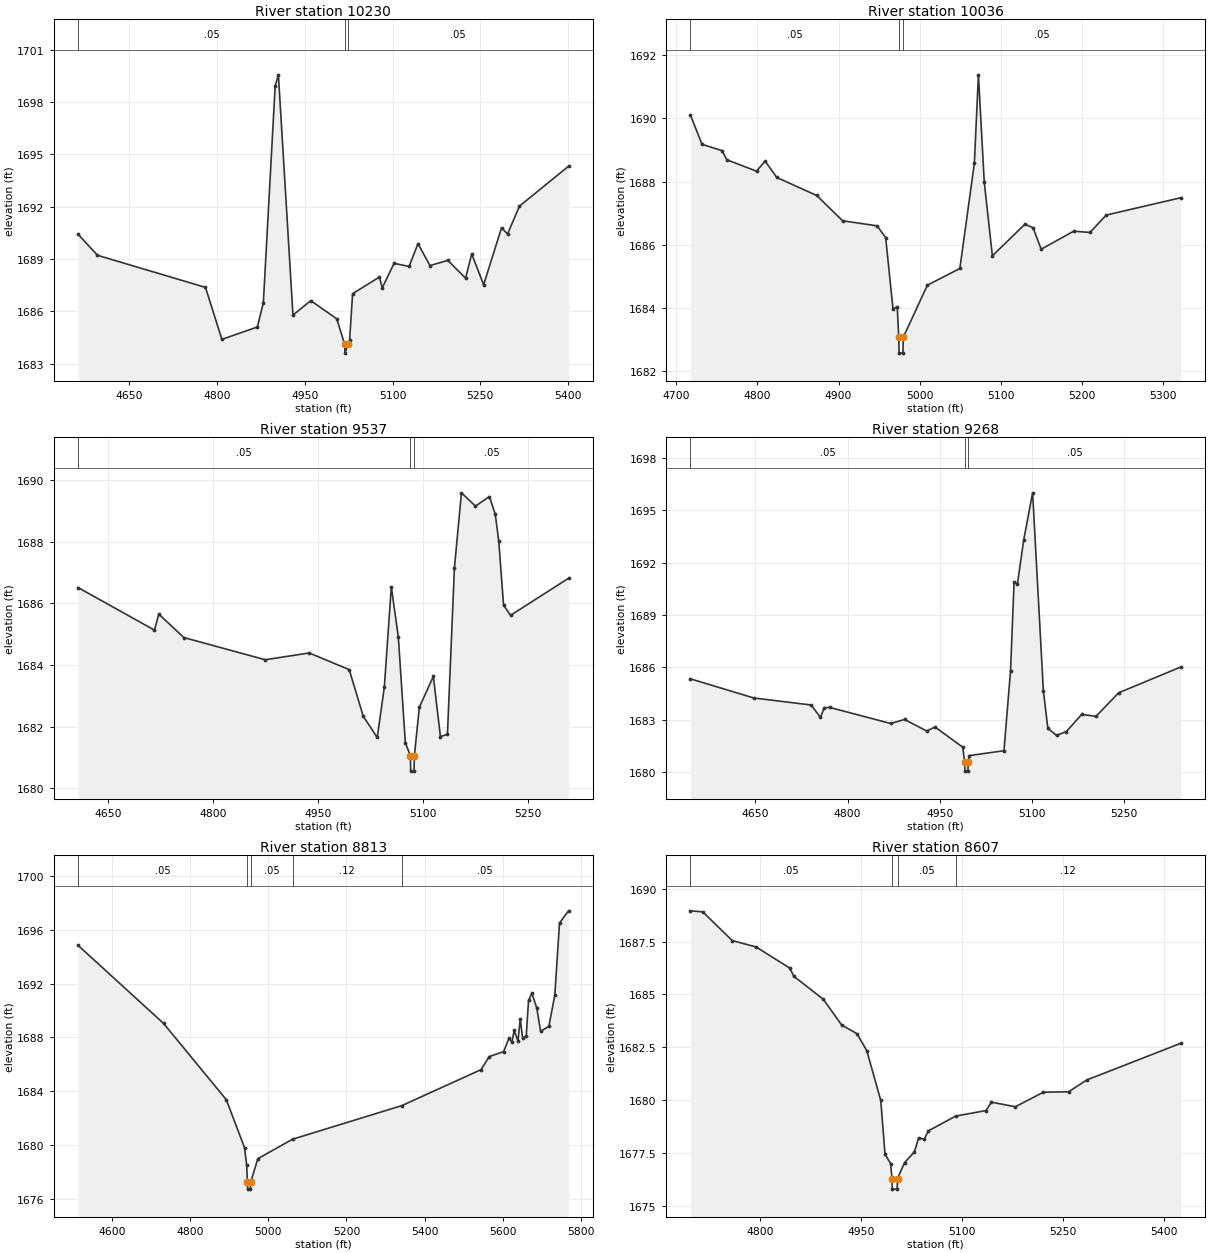
Type RM Length L Ch R = 1,10230,194,194,194
BEGIN DESCRIPTION:
Mapping XS f79e1b59
END DESCRIPTION:
XS GIS Cut Line= 3
      1625113.71      6899745.24      1625044.46      6900181.84
      1624966.17      6900570.27
#Sta/Elev= 30
  4562.5 1690.42  4595.7 1689.21  4780.3 1687.37  4808.3 1684.39  4869.0 1685.10
  4879.2 1686.50  4899.4 1698.93  4904.9 1699.56  4929.8 1685.78  4960.2 1686.61
  5004.6 1685.57  5018.2 1684.10  5018.7 1683.60  5023.8 1684.10  5026.6 1684.33
  5031.7 1687.01  5077.4 1687.96  5082.5 1687.35  5102.6 1688.75  5128.3 1688.57
  5143.5 1689.88  5163.9 1688.62  5194.5 1688.92  5224.8 1687.90  5235.3 1689.29
  5255.7 1687.52  5286.3 1690.79  5296.5 1690.43  5316.9 1692.03  5400.8 1694.32
#Mann=3,-1,0
  4562.5    0.05       0  5018.2    0.03       0  5023.8    0.05       0
Bank Sta=5018.2,5023.8
Exp/Cntr=0.3,0.1

Type RM Length L Ch R = 1,10036,499,499,499
BEGIN DESCRIPTION:
Deadman 49 17.0
END DESCRIPTION:
XS GIS Cut Line= 3
      1625065.41      6899741.26      1624976.88      6899988.64
      1624950.84      6900329.81
#Sta/Elev= 30
  4717.3 1690.11  4731.6 1689.18  4756.3 1688.98  4762.3 1688.69  4798.8 1688.33
  4809.4 1688.65  4823.9 1688.13  4873.1 1687.56  4905.0 1686.76  4947.5 1686.60
  4958.1 1686.23  4967.1 1683.98  4972.4 1684.03  4974.2 1683.07  4974.7 1682.57
  4979.4 1682.57  4979.8 1683.07  5009.5 1684.72  5049.6 1685.25  5067.5 1688.58
  5072.5 1691.38  5079.7 1687.98  5089.7 1685.65  5129.8 1686.65  5139.9 1686.54
  5149.9 1685.86  5190.0 1686.43  5210.1 1686.39  5230.1 1686.94  5322.2 1687.49
#Mann=3,-1,0
  4717.3    0.05       0  4974.2    0.03       0  4979.8    0.05       0
Bank Sta=4974.2,4979.8
Exp/Cntr=0.3,0.1

Type RM Length L Ch R = 1,9537,269,269,269
BEGIN DESCRIPTION:
Mapping XS d35b1078
END DESCRIPTION:
XS GIS Cut Line= 3
      1624725.31      6899657.96      1624510.73      6899967.81
      1624495.11      6900290.74
#Sta/Elev= 30
  4607.5 1686.51  4716.6 1685.13  4722.7 1685.65  4758.5 1684.89  4874.7 1684.17
  4937.5 1684.39  4994.6 1683.85  5014.6 1682.34  5034.6 1681.65  5044.7 1683.28
  5054.7 1686.53  5064.7 1684.91  5074.7 1681.48  5081.9 1681.06  5082.4 1680.56
  5087.1 1680.56  5087.6 1681.06  5094.7 1682.63  5114.7 1683.63  5124.8 1681.68
  5134.8 1681.75  5144.8 1687.15  5154.8 1689.58  5174.8 1689.15  5194.8 1689.46
  5203.1 1688.88  5208.1 1688.01  5214.9 1685.94  5224.9 1685.61  5307.7 1686.81
#Mann=3,-1,0
  4607.5    0.05       0  5081.9    0.03       0  5087.6    0.05       0
Bank Sta=5081.9,5087.6
Exp/Cntr=0.3,0.1

Type RM Length L Ch R = 1,9268,455,455,455
BEGIN DESCRIPTION:
Deadman 49 16.0
END DESCRIPTION:
XS GIS Cut Line= 3
      1624635.00      6899685.05      1624255.00      6899938.00
      1624376.06      6900257.11
#Sta/Elev= 30
  4544.4 1685.34  4647.7 1684.24  4740.9 1683.84  4755.9 1683.13  4762.0 1683.68
  4771.0 1683.70  4870.2 1682.78  4892.8 1683.01  4928.8 1682.35  4942.3 1682.58
  4987.4 1681.42  4990.5 1680.55  4991.0 1680.05  4995.8 1680.05  4996.2 1680.55
  4997.9 1680.94  5054.4 1681.22  5065.1 1685.79  5070.9 1690.91  5076.2 1690.76
  5086.5 1693.29  5101.0 1696.00  5118.5 1684.66  5125.8 1682.50  5139.9 1682.10
  5156.0 1682.32  5180.8 1683.30  5204.1 1683.19  5241.0 1684.54  5342.2 1686.02
#Mann=3,-1,0
  4544.4    0.05       0  4990.5    0.05       0  4996.2    0.05       0
Bank Sta=4990.5,4996.2
Exp/Cntr=0.3,0.1

Type RM Length L Ch R = 1,8813,206,206,206
BEGIN DESCRIPTION:
Deadman 49 15.0
END DESCRIPTION:
XS GIS Cut Line= 3
      1623654.99      6899537.97      1623855.00      6899988.00
      1624505.01      6900388.00
#Sta/Elev= 30
  4512.9 1694.83  4731.8 1689.04  4892.5 1683.38  4939.0 1679.83  4944.5 1678.55
  4946.6 1677.25  4947.1 1676.75  4954.2 1676.75  4954.7 1677.25  4973.2 1679.01
  5061.9 1680.45  5342.3 1682.95  5544.4 1685.61  5565.7 1686.58  5602.4 1686.95
  5615.9 1687.94  5623.7 1687.66  5629.5 1688.53  5639.1 1687.72  5644.9 1689.35
  5651.2 1687.93  5660.3 1688.11  5666.2 1690.75  5674.7 1691.28  5687.5 1690.16
  5697.0 1688.45  5718.3 1688.83  5733.4 1691.13  5745.5 1696.49  5768.6 1697.39
#Mann=5,-1,0
  4512.9    0.05       0  4946.6    0.05       0  4954.7    0.05       0
  5061.9    0.12       0  5342.3    0.05       0
Bank Sta=4946.6,4954.7
Exp/Cntr=0.3,0.1

Type RM Length L Ch R = 1,8607,238,238,238
BEGIN DESCRIPTION:
Mapping XS 3a256089
END DESCRIPTION:
XS GIS Cut Line= 2
      1623508.99      6899858.22      1623946.51      6900441.58
#Sta/Elev= 30
  4696.0 1688.96  4714.4 1688.91  4758.2 1687.55  4793.6 1687.25  4843.6 1686.25
  4849.8 1685.86  4893.6 1684.77  4920.7 1683.56  4943.6 1683.14  4958.2 1682.34
  4979.0 1679.98  4985.3 1677.44  4993.6 1676.99  4995.7 1676.28  4996.2 1675.78
  5003.4 1675.78  5003.9 1676.28  5014.4 1677.04  5029.0 1677.54  5035.3 1678.21
  5043.6 1678.14  5049.8 1678.54  5090.4 1679.24  5135.3 1679.50  5143.6 1679.90
  5179.0 1679.68  5220.7 1680.37  5258.2 1680.39  5285.3 1680.95  5425.2 1682.69
#Mann=4,-1,0
  4696.0    0.05       0  4995.7    0.05       0  5003.9    0.05       0
  5090.4    0.12       0
Bank Sta=4995.7,5003.9
Exp/Cntr=0.3,0.1