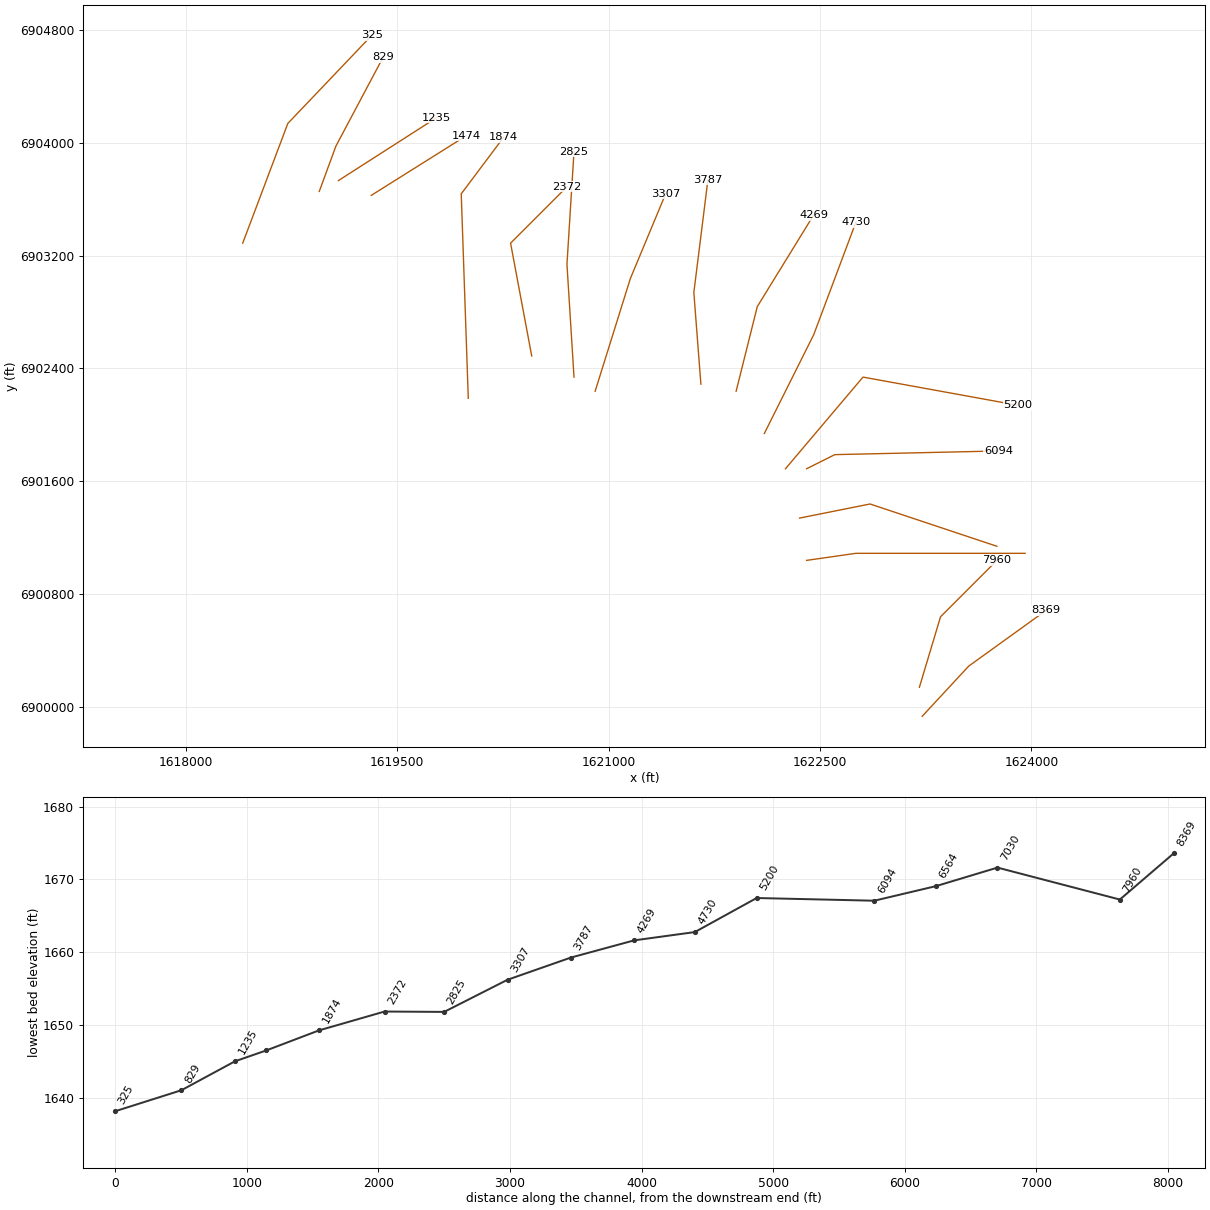
HEC-RAS study Deadman 49.prj: Deadman 49 Base Level Engineering

--- Deadman 49.g01 (geometry) --- (continued)

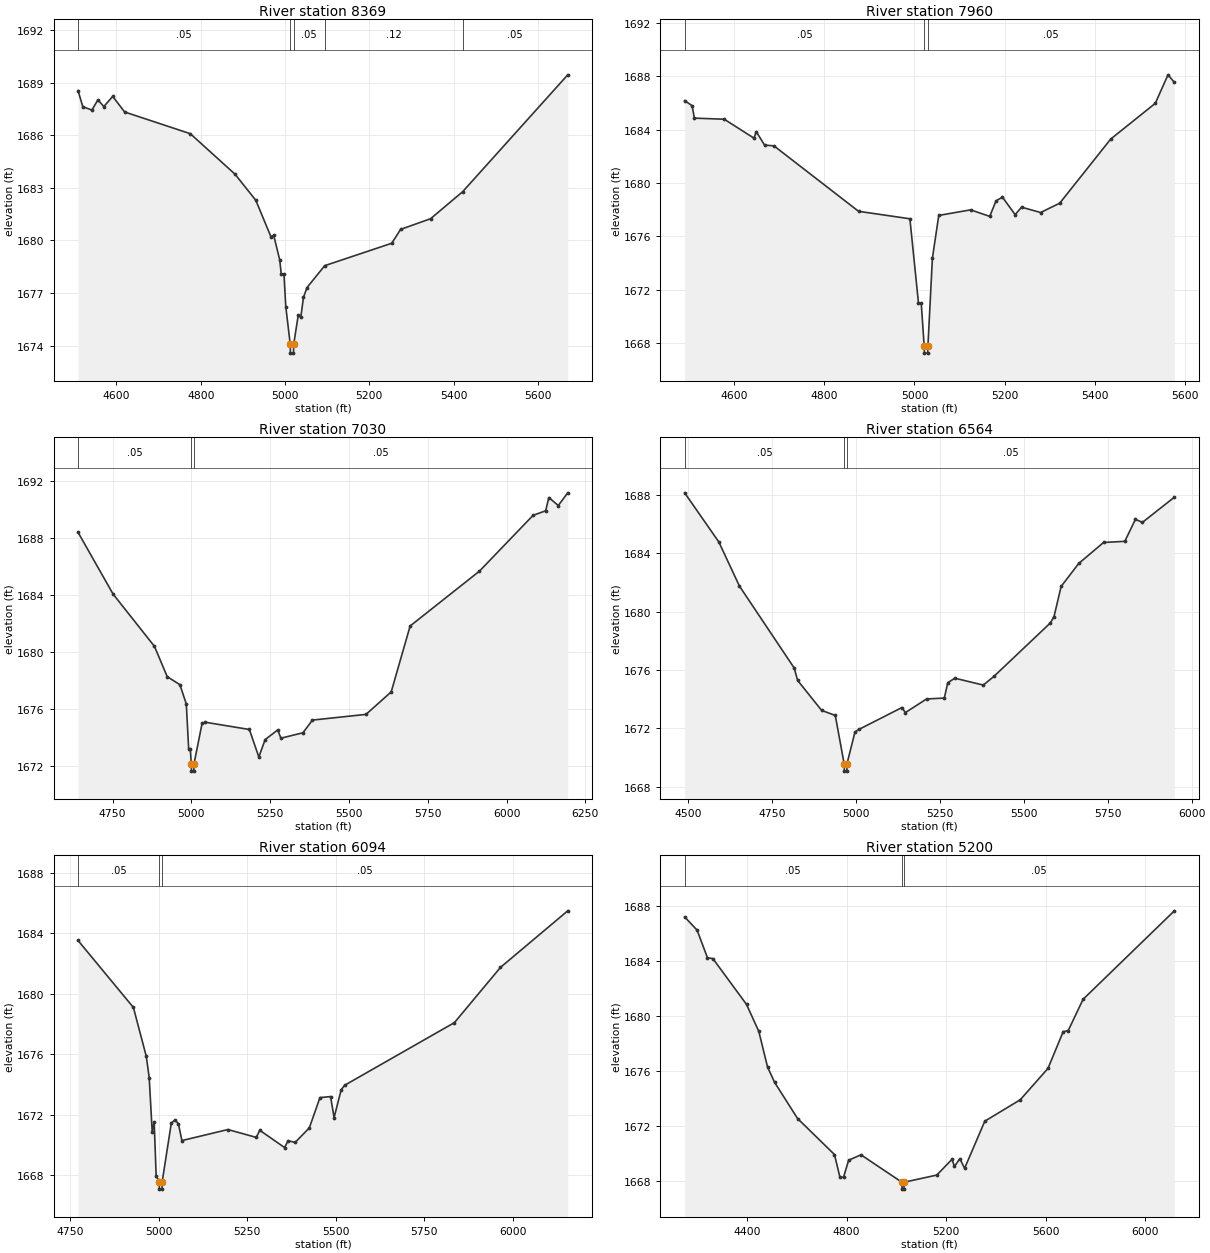
Type RM Length L Ch R = 1,8369,409,409,409
BEGIN DESCRIPTION:
Deadman 49 14.0
END DESCRIPTION:
XS GIS Cut Line= 3
      1623224.70      6899931.96      1623555.00      6900288.00
      1624103.85      6900683.38
#Sta/Elev= 30
  4508.8 1688.55  4520.2 1687.63  4541.8 1687.44  4555.9 1688.02  4570.1 1687.64
  4591.1 1688.22  4619.4 1687.33  4775.3 1686.09  4881.4 1683.78  4930.7 1682.29
  4966.4 1680.22  4973.2 1680.29  4987.4 1678.89  4991.1 1678.07  4997.5 1678.07
  5001.8 1676.23  5012.4 1674.07  5012.9 1673.57  5020.1 1673.57  5020.6 1674.07
  5031.3 1675.73  5037.4 1675.61  5043.8 1676.75  5052.1 1677.31  5094.2 1678.56
  5253.3 1679.84  5274.3 1680.63  5345.4 1681.24  5421.5 1682.78  5670.9 1689.45
#Mann=5,-1,0
  4508.8    0.05       0  5012.4    0.03       0  5020.6    0.05       0
  5094.2    0.12       0  5421.5    0.05       0
Bank Sta=5012.4,5020.6
Exp/Cntr=0.3,0.1

Type RM Length L Ch R = 1,7960,930,930,930
BEGIN DESCRIPTION:
Deadman 49 13.0
END DESCRIPTION:
XS GIS Cut Line= 3
      1623205.00      6900138.00      1623355.00      6900638.00
      1623755.00      6901038.00
#Sta/Elev= 30
  4489.5 1686.17  4506.0 1685.80  4511.2 1684.86  4577.4 1684.78  4643.5 1683.36
  4648.7 1683.84  4667.0 1682.84  4687.9 1682.78  4875.8 1677.87  4989.8 1677.31
  5008.9 1670.98  5015.0 1670.98  5021.6 1667.73  5022.1 1667.23  5029.3 1667.23
  5029.8 1667.73  5039.8 1674.35  5053.9 1677.56  5124.7 1677.98  5167.1 1677.49
  5181.2 1678.66  5195.4 1678.93  5223.6 1677.62  5237.8 1678.18  5280.2 1677.78
  5322.6 1678.48  5435.8 1683.29  5534.8 1685.97  5563.1 1688.11  5577.2 1687.54
#Mann=3,-1,0
  4489.5    0.05       0  5021.6    0.05       0  5029.8    0.05       0
Bank Sta=5021.6,5029.8
Exp/Cntr=0.3,0.1

Type RM Length L Ch R = 1,7030,466,466,466
BEGIN DESCRIPTION:
Deadman 49 12.0
END DESCRIPTION:
XS GIS Cut Line= 3
      1622404.96      6901037.99      1622755.00      6901088.00
      1623955.00      6901088.00
#Sta/Elev= 30
  4640.4 1688.37  4751.6 1684.04  4882.9 1680.37  4923.3 1678.25  4963.7 1677.68
  4983.9 1676.33  4991.5 1673.16  4996.5 1673.16  4999.8 1672.12  5000.3 1671.62
  5007.7 1671.62  5008.2 1672.12  5034.0 1674.97  5044.0 1675.05  5184.0 1674.54
  5214.0 1672.61  5234.0 1673.83  5274.0 1674.51  5284.0 1673.93  5354.0 1674.31
  5384.0 1675.20  5554.0 1675.60  5634.0 1677.18  5694.0 1681.80  5914.0 1685.65
  6084.0 1689.56  6124.0 1689.88  6134.0 1690.81  6164.0 1690.25  6194.0 1691.14
#Mann=3,-1,0
  4640.4    0.05       0  4999.8    0.05       0  5008.2    0.05       0
Bank Sta=4999.8,5008.2
Exp/Cntr=0.3,0.1

Type RM Length L Ch R = 1,6564,470,470,470
BEGIN DESCRIPTION:
Deadman 49 11.0
END DESCRIPTION:
XS GIS Cut Line= 3
      1622355.02      6901338.00      1622855.00      6901438.00
      1623755.03      6901137.99
#Sta/Elev= 30
  4489.9 1688.13  4591.9 1684.76  4653.0 1681.75  4816.2 1676.14  4826.4 1675.29
  4897.8 1673.24  4938.6 1672.89  4965.0 1669.58  4965.5 1669.08  4972.9 1669.08
  4973.4 1669.58  4997.2 1671.76  5010.3 1671.95  5136.8 1673.43  5147.4 1673.09
  5210.6 1674.02  5263.3 1674.08  5273.8 1675.14  5294.9 1675.44  5379.3 1674.97
  5410.9 1675.56  5579.5 1679.23  5590.1 1679.66  5611.2 1681.72  5663.9 1683.30
  5737.6 1684.73  5800.9 1684.81  5832.5 1686.31  5853.6 1686.11  5948.5 1687.83
#Mann=3,-1,0
  4489.9    0.05       0  4965.0    0.03       0  4973.4    0.05       0
Bank Sta=4965,4973.4
Exp/Cntr=0.3,0.1

Type RM Length L Ch R = 1,6094,894,894,894
BEGIN DESCRIPTION:
Deadman 49 10.0
END DESCRIPTION:
XS GIS Cut Line= 3
      1622405.00      6901688.00      1622605.00      6901788.00
      1623765.10      6901814.02
#Sta/Elev= 30
  4772.0 1683.51  4928.5 1679.08  4964.9 1675.85  4973.2 1674.43  4981.6 1670.86
  4987.2 1671.52  4992.8 1667.95  5001.4 1667.57  5001.9 1667.07  5009.4 1667.07
  5009.9 1667.57  5035.6 1671.43  5045.6 1671.64  5055.6 1671.40  5065.6 1670.28
  5195.7 1671.01  5275.7 1670.49  5285.7 1670.96  5355.7 1669.82  5365.7 1670.27
  5385.7 1670.16  5425.7 1671.12  5455.7 1673.12  5485.7 1673.19  5495.7 1671.80
  5515.7 1673.64  5525.7 1673.94  5835.8 1678.08  5965.9 1681.73  6156.0 1685.47
#Mann=3,-1,0
  4772.0    0.05       0  5001.4    0.03       0  5009.9    0.05       0
Bank Sta=5001.4,5009.9
Exp/Cntr=0.3,0.1

Type RM Length L Ch R = 1,5200,470,470,470
BEGIN DESCRIPTION:
Deadman 49 9.0
END DESCRIPTION:
XS GIS Cut Line= 3
      1622255.01      6901688.01      1622805.00      6902338.00
      1623905.01      6902138.00
#Sta/Elev= 30
  4148.7 1687.19  4198.7 1686.23  4240.4 1684.23  4262.4 1684.16  4397.6 1680.84
  4447.0 1678.88  4482.1 1676.30  4510.7 1675.18  4603.0 1672.56  4751.3 1669.95
  4773.3 1668.30  4787.6 1668.30  4808.4 1669.54  4857.9 1669.93  5022.5 1667.94
  5023.0 1667.44  5030.7 1667.44  5031.2 1667.94  5162.8 1668.46  5223.8 1669.60
  5233.9 1669.09  5255.5 1669.65  5274.6 1668.95  5355.9 1672.37  5498.2 1673.92
  5610.0 1676.20  5671.0 1678.86  5691.3 1678.94  5751.0 1681.21  6118.2 1687.63
#Mann=3,-1,0
  4148.7    0.05       0  5022.5    0.03       0  5031.2    0.05       0
Bank Sta=5022.5,5031.2
Exp/Cntr=0.3,0.1

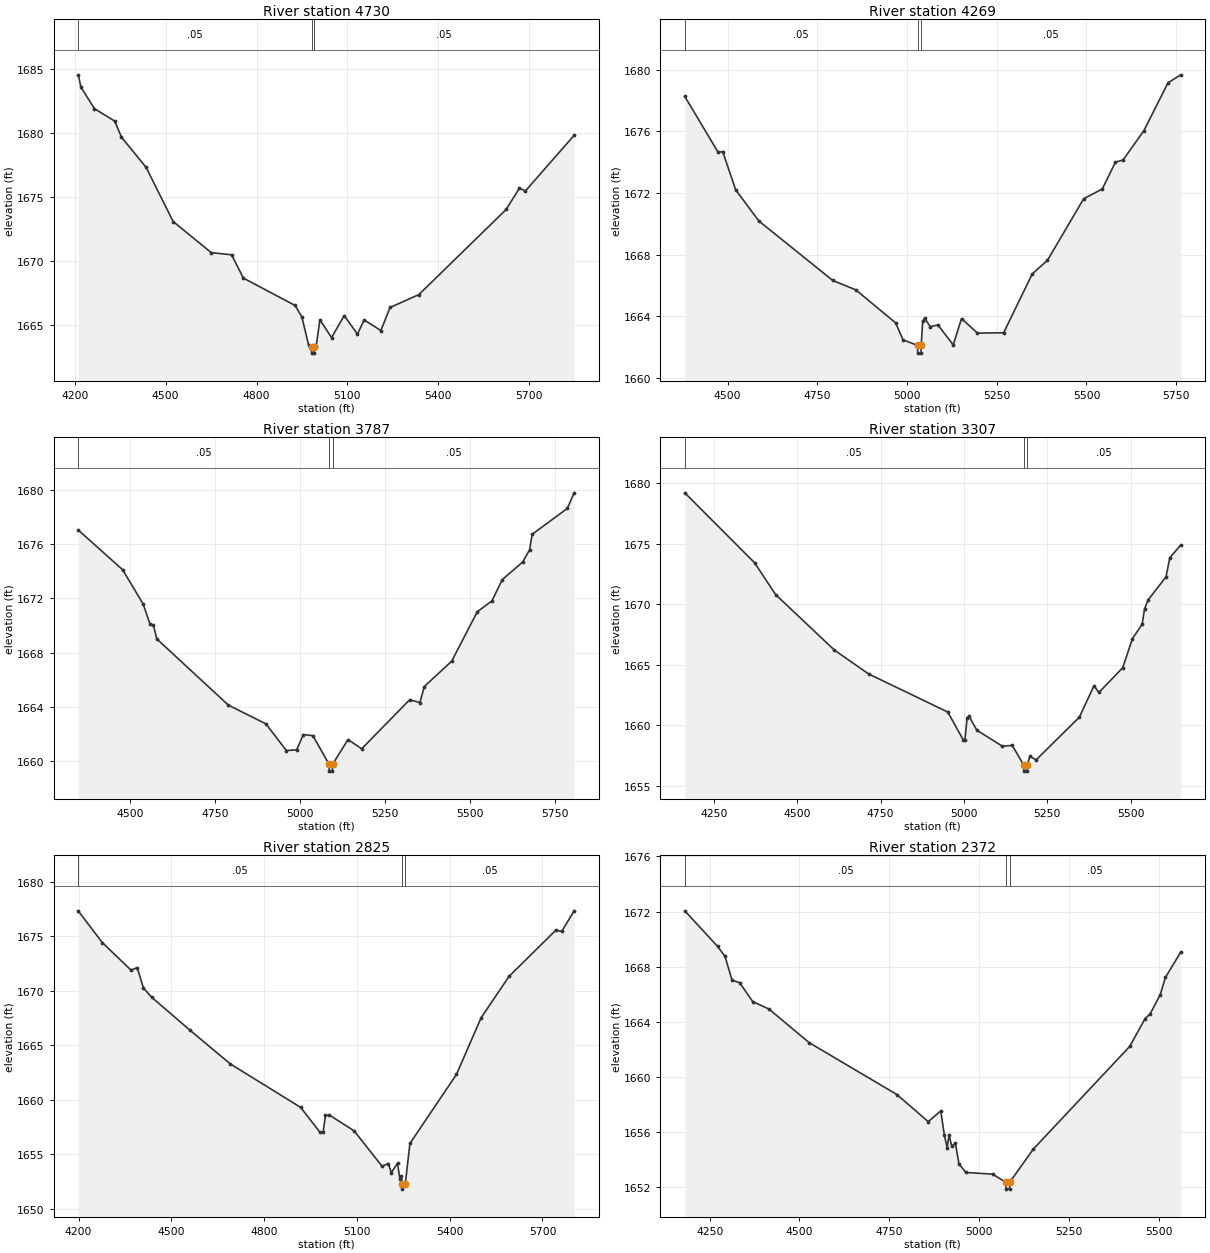
Type RM Length L Ch R = 1,4730,461,461,461
BEGIN DESCRIPTION:
Deadman 49 8.0
END DESCRIPTION:
XS GIS Cut Line= 3
      1622105.00      6901938.01      1622455.00      6902638.00
      1622755.00      6903437.99
#Sta/Elev= 30
  4211.7 1684.58  4220.1 1683.62  4264.8 1681.93  4331.9 1680.95  4354.2 1679.69
  4435.3 1677.33  4524.7 1673.08  4650.5 1670.64  4717.6 1670.47  4756.7 1668.64
  4927.2 1666.50  4949.6 1665.61  4972.0 1663.39  4981.6 1663.26  4982.1 1662.76
  4989.8 1662.76  4990.3 1663.26  4997.0 1663.32  5009.4 1665.37  5047.7 1663.98
  5089.5 1665.70  5133.2 1664.25  5155.4 1665.36  5210.6 1664.53  5240.8 1666.34
  5336.1 1667.35  5624.4 1674.03  5668.0 1675.70  5687.6 1675.47  5848.7 1679.84
#Mann=3,-1,0
  4211.7    0.05       0  4981.6    0.05       0  4990.3    0.05       0
Bank Sta=4981.6,4990.3
Exp/Cntr=0.3,0.1

Type RM Length L Ch R = 1,4269,482,482,482
BEGIN DESCRIPTION:
Deadman 49 7.0
END DESCRIPTION:
XS GIS Cut Line= 3
      1621905.00      6902238.00      1622055.00      6902838.00
      1622455.01      6903488.02
#Sta/Elev= 30
  4380.6 1678.26  4473.4 1674.64  4486.3 1674.68  4522.3 1672.21  4586.8 1670.19
  4792.9 1666.33  4857.3 1665.72  4968.1 1663.58  4988.8 1662.48  5029.3 1662.12
  5029.8 1661.62  5038.8 1661.62  5039.3 1662.12  5043.5 1663.69  5049.3 1663.88
  5064.7 1663.33  5086.0 1663.45  5128.6 1662.15  5151.7 1663.86  5196.1 1662.92
  5269.1 1662.94  5348.7 1666.75  5391.3 1667.64  5492.2 1671.63  5544.0 1672.26
  5580.6 1674.00  5601.9 1674.14  5659.9 1676.04  5727.1 1679.14  5762.3 1679.66
#Mann=3,-1,0
  4380.6    0.05       0  5029.3    0.05       0  5039.3    0.05       0
Bank Sta=5029.3,5039.3
Exp/Cntr=0.3,0.1

Type RM Length L Ch R = 1,3787,480,480,480
BEGIN DESCRIPTION:
Deadman 49 6.0
END DESCRIPTION:
XS GIS Cut Line= 3
      1621655.00      6902288.03      1621605.00      6902938.00
      1621705.00      6903737.98
#Sta/Elev= 30
  4348.6 1677.04  4479.0 1674.11  4539.1 1671.59  4559.2 1670.11  4569.2 1670.04
  4579.3 1669.01  4789.9 1664.12  4900.2 1662.74  4960.4 1660.77  4990.5 1660.82
  5010.6 1661.95  5038.3 1661.87  5086.1 1659.75  5086.6 1659.25  5095.7 1659.25
  5096.2 1659.75  5141.6 1661.58  5181.9 1660.90  5323.0 1664.52  5353.2 1664.31
  5365.8 1665.49  5446.4 1667.36  5522.0 1671.02  5564.9 1671.81  5595.1 1673.38
  5655.6 1674.69  5675.7 1675.59  5683.3 1676.73  5786.6 1678.64  5806.7 1679.79
#Mann=3,-1,0
  4348.6    0.05       0  5086.1    0.05       0  5096.2    0.05       0
Bank Sta=5086.1,5096.2
Exp/Cntr=0.3,0.1

Type RM Length L Ch R = 1,3307,482,482,482
BEGIN DESCRIPTION:
Deadman 49 5.0
END DESCRIPTION:
XS GIS Cut Line= 3
      1620905.01      6902238.02      1621155.00      6903038.00
      1621404.99      6903637.98
#Sta/Elev= 30
  4162.1 1679.20  4371.6 1673.42  4434.5 1670.80  4611.0 1666.21  4713.7 1664.24
  4951.5 1661.09  4997.6 1658.80  5002.9 1658.80  5009.4 1660.61  5014.9 1660.75
  5038.7 1659.59  5115.6 1658.26  5144.9 1658.34  5179.3 1656.71  5179.8 1656.21
  5189.0 1656.21  5189.5 1656.71  5197.9 1657.44  5216.4 1657.14  5346.4 1660.67
  5390.2 1663.26  5404.9 1662.71  5476.4 1664.75  5505.6 1667.15  5534.9 1668.36
  5541.9 1669.61  5552.7 1670.36  5606.4 1672.26  5617.7 1673.83  5650.2 1674.88
#Mann=3,-1,0
  4162.1    0.05       0  5179.3    0.05       0  5189.5    0.05       0
Bank Sta=5179.3,5189.5
Exp/Cntr=0.3,0.1

Type RM Length L Ch R = 1,2825,453,453,453
BEGIN DESCRIPTION:
Deadman 49 4.0
END DESCRIPTION:
XS GIS Cut Line= 3
      1620755.00      6902337.99      1620705.00      6903138.00
      1620755.00      6903937.97
#Sta/Elev= 30
  4199.3 1677.31  4277.0 1674.41  4369.6 1671.89  4389.7 1672.12  4409.7 1670.25
  4437.3 1669.38  4560.0 1666.38  4690.3 1663.29  4918.2 1659.29  4980.8 1657.00
  4990.8 1657.05  4998.4 1658.55  5010.9 1658.59  5091.0 1657.14  5181.2 1653.89
  5201.3 1654.14  5211.3 1653.30  5231.3 1654.17  5238.8 1652.73  5243.8 1652.97
  5246.3 1652.29  5246.8 1651.79  5256.5 1652.29  5271.4 1655.98  5421.7 1662.31
  5501.8 1667.53  5592.0 1671.32  5742.3 1675.53  5762.3 1675.45  5802.4 1677.33
#Mann=3,-1,0
  4199.3    0.05       0  5246.3    0.05       0  5256.5    0.05       0
Bank Sta=5246.3,5256.5
Exp/Cntr=0.3,0.1

Type RM Length L Ch R = 1,2372,498,498,498
BEGIN DESCRIPTION:
Deadman 49 3.0
END DESCRIPTION:
XS GIS Cut Line= 3
      1620455.00      6902488.02      1620305.00      6903288.00
      1620705.00      6903688.00
#Sta/Elev= 30
  4180.9 1672.05  4272.4 1669.46  4292.8 1668.74  4312.3 1667.02  4333.5 1666.83
  4369.9 1665.46  4414.9 1664.92  4526.8 1662.48  4771.0 1658.71  4858.3 1656.74
  4893.1 1657.52  4903.2 1655.74  4910.9 1654.86  4916.0 1655.76  4923.6 1654.97
  4933.8 1655.16  4943.9 1653.66  4963.4 1653.05  5037.2 1652.93  5074.3 1652.34
  5074.8 1651.84  5084.5 1651.84  5085.0 1652.34  5150.4 1654.74  5419.1 1662.21
  5461.5 1664.22  5475.6 1664.56  5503.9 1665.97  5518.1 1667.21  5560.5 1669.04
#Mann=3,-1,0
  4180.9    0.05       0  5074.3    0.05       0  5085.0    0.05       0
Bank Sta=5074.3,5085
Exp/Cntr=0.3,0.1

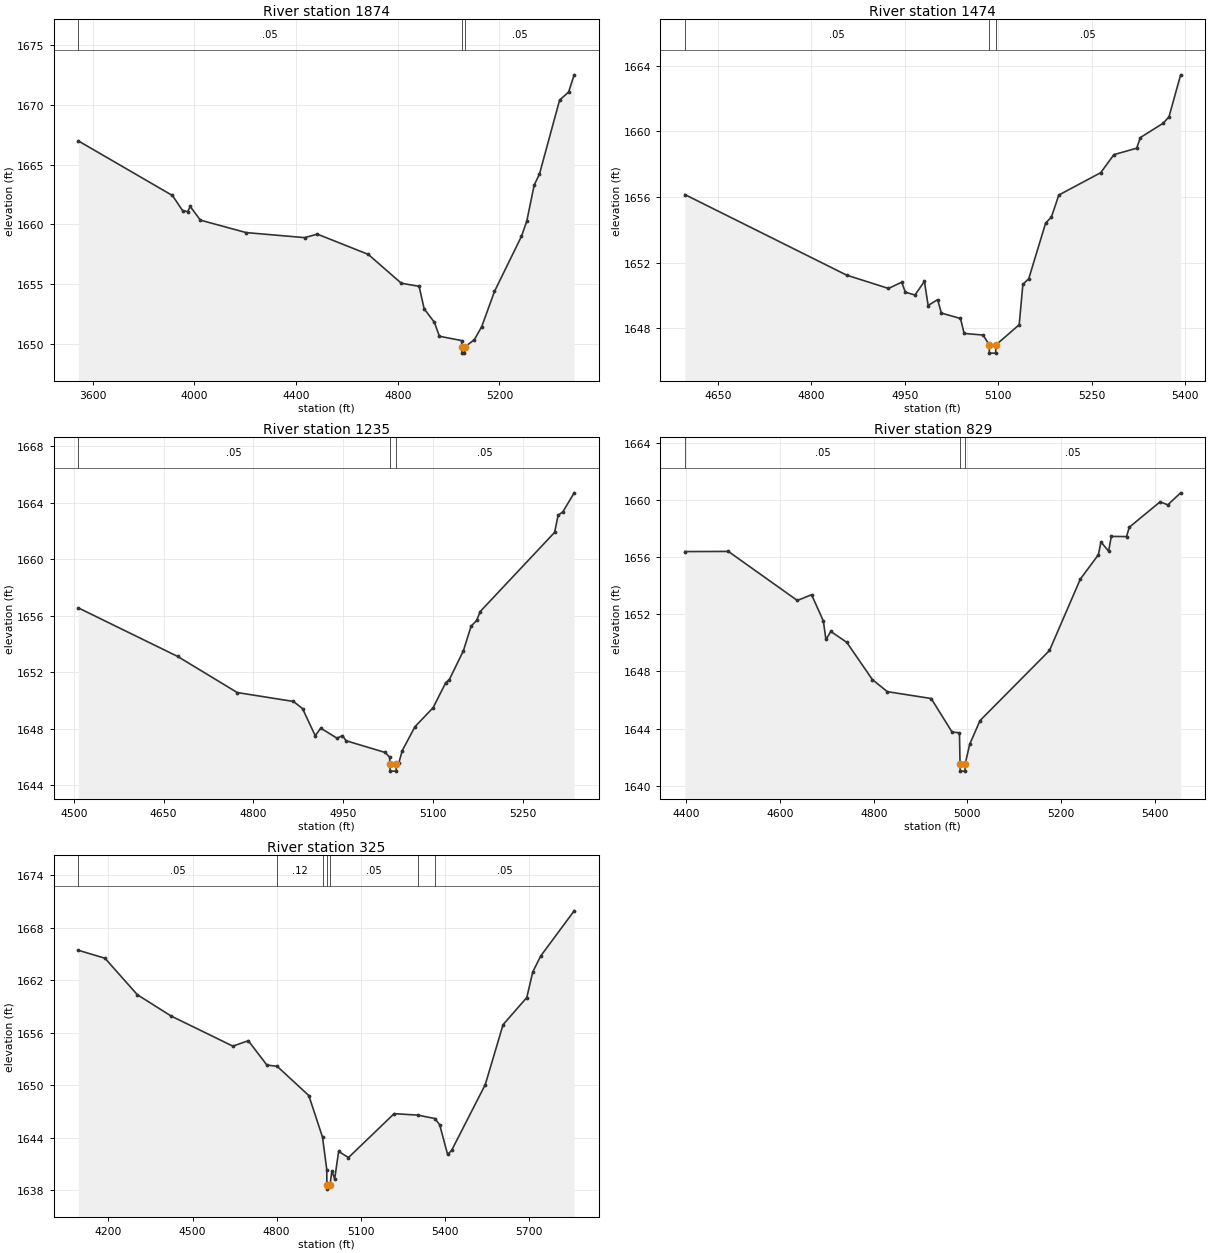
Type RM Length L Ch R = 1,1874,400,400,400
BEGIN DESCRIPTION:
Deadman 49 2.0
END DESCRIPTION:
XS GIS Cut Line= 3
      1620005.00      6902188.01      1619955.00      6903638.00
      1620255.03      6904038.04
#Sta/Elev= 30
  3543.3 1666.98  3913.5 1662.42  3953.5 1661.16  3973.5 1661.07  3983.6 1661.50
  4023.6 1660.36  4203.7 1659.32  4433.8 1658.90  4483.8 1659.19  4684.0 1657.50
  4814.0 1655.09  4884.1 1654.83  4904.1 1652.95  4944.1 1651.83  4964.1 1650.66
  5051.4 1650.30  5052.3 1649.75  5052.8 1649.25  5062.5 1649.25  5063.0 1649.75
  5101.4 1650.37  5130.6 1651.47  5180.6 1654.40  5286.9 1659.01  5307.7 1660.27
  5336.9 1663.29  5357.7 1664.21  5436.9 1670.39  5472.3 1671.06  5494.2 1672.50
#Mann=3,-1,0
  3543.3    0.05       0  5052.3    0.05       0  5063.0    0.05       0
Bank Sta=5052.3,5063
Exp/Cntr=0.3,0.1

Type RM Length L Ch R = 1,1474,239,239,239
BEGIN DESCRIPTION:
Mapping XS 466fd15e
END DESCRIPTION:
XS GIS Cut Line= 2
      1619316.82      6903626.98      1619990.54      6904049.97
#Sta/Elev= 30
  4596.9 1656.16  4856.6 1651.25  4923.7 1650.44  4944.9 1650.82  4950.8 1650.21
  4966.1 1650.04  4981.4 1650.87  4987.3 1649.40  5002.6 1649.76  5008.5 1648.94
  5039.2 1648.61  5045.1 1647.70  5075.7 1647.60  5085.2 1647.00  5085.7 1646.50
  5095.6 1646.50  5096.1 1647.00  5133.4 1648.23  5139.3 1650.69  5148.7 1651.03
  5175.8 1654.42  5185.1 1654.79  5197.0 1656.13  5264.2 1657.49  5285.4 1658.59
  5321.9 1658.98  5327.8 1659.63  5364.3 1660.50  5373.7 1660.89  5392.4 1663.45
#Mann=3,-1,0
  4596.9    0.05       0  5085.2    0.05       0  5096.1    0.05       0
Bank Sta=5085.2,5096.1
Exp/Cntr=0.3,0.1

Type RM Length L Ch R = 1,1235,406,406,406
BEGIN DESCRIPTION:
Mapping XS 5edd69b8
END DESCRIPTION:
XS GIS Cut Line= 2
      1619083.36      6903731.74      1619780.82      6904178.55
#Sta/Elev= 30
  4507.5 1656.55  4673.2 1653.12  4773.0 1650.56  4866.9 1649.93  4882.1 1649.42
  4903.2 1647.51  4912.5 1648.04  4939.6 1647.33  4948.8 1647.51  4954.8 1647.15
  5020.1 1646.32  5027.5 1645.98  5028.0 1645.50  5028.5 1645.00  5038.4 1645.00
  5038.9 1645.50  5042.7 1645.55  5048.6 1646.45  5069.8 1648.14  5100.2 1649.49
  5121.3 1651.26  5127.3 1651.48  5150.7 1653.51  5163.6 1655.25  5172.9 1655.66
  5178.8 1656.29  5303.1 1661.89  5309.0 1663.10  5317.0 1663.35  5335.8 1664.69
#Mann=3,-1,0
  4507.5    0.05       0  5028.0    0.05       0  5038.9    0.05       0
Bank Sta=5028,5038.9
Exp/Cntr=0.3,0.1

Type RM Length L Ch R = 1,829,504,504,504
BEGIN DESCRIPTION:
Mapping XS ce4f6f6b
END DESCRIPTION:
XS GIS Cut Line= 3
      1618948.04      6903655.32      1619065.89      6903976.12
      1619401.95      6904608.96
#Sta/Elev= 30
  4396.8 1656.39  4489.8 1656.40  4636.9 1652.97  4667.4 1653.37  4692.6 1651.53
  4698.0 1650.24  4708.6 1650.80  4742.5 1650.04  4797.3 1647.43  4829.1 1646.59
  4922.7 1646.11  4967.1 1643.77  4983.0 1643.71  4984.3 1641.53  4984.8 1641.03
  4994.7 1641.03  4995.2 1641.53  5005.0 1642.92  5027.0 1644.57  5175.2 1649.47
  5241.1 1654.47  5279.4 1656.16  5285.1 1657.06  5301.4 1656.42  5307.1 1657.45
  5339.7 1657.44  5345.4 1658.09  5411.3 1659.87  5427.7 1659.66  5455.1 1660.50
#Mann=3,-1,0
  4396.8    0.05       0  4984.3    0.05       0  4995.2    0.05       0
Bank Sta=4984.3,4995.2
Exp/Cntr=0.3,0.1

Type RM Length L Ch R = 1,325,0,0,0
BEGIN DESCRIPTION:
Deadman 49 1.0
END DESCRIPTION:
XS GIS Cut Line= 3
      1618405.00      6903287.99      1618725.04      6904137.39
      1619320.12      6904761.72
#Sta/Elev= 30
  4092.3 1665.45  4187.4 1664.54  4302.9 1660.37  4423.7 1657.93  4644.0 1654.49
  4699.1 1655.11  4765.5 1652.33  4802.3 1652.18  4915.2 1648.84  4964.1 1644.08
  4979.3 1640.37  4979.7 1638.64  4980.2 1638.14  4990.7 1638.64  4997.7 1640.22
  5007.5 1639.31  5021.6 1642.45  5056.8 1641.75  5219.8 1646.77  5304.8 1646.60
  5365.4 1646.21  5382.4 1645.50  5410.7 1642.10  5424.8 1642.56  5545.0 1650.08
  5608.7 1656.94  5693.4 1660.05  5714.8 1662.98  5743.2 1664.80  5862.5 1669.96
#Mann=7,-1,0
  4092.3    0.05       0  4802.3    0.12       0  4964.1    0.05       0
  4979.7    0.05       0  4990.7    0.05       0  5304.8    0.12       0
  5365.4    0.05       0
Bank Sta=4979.7,4990.7
Exp/Cntr=0.3,0.1

Chan Stop Cuts=-1