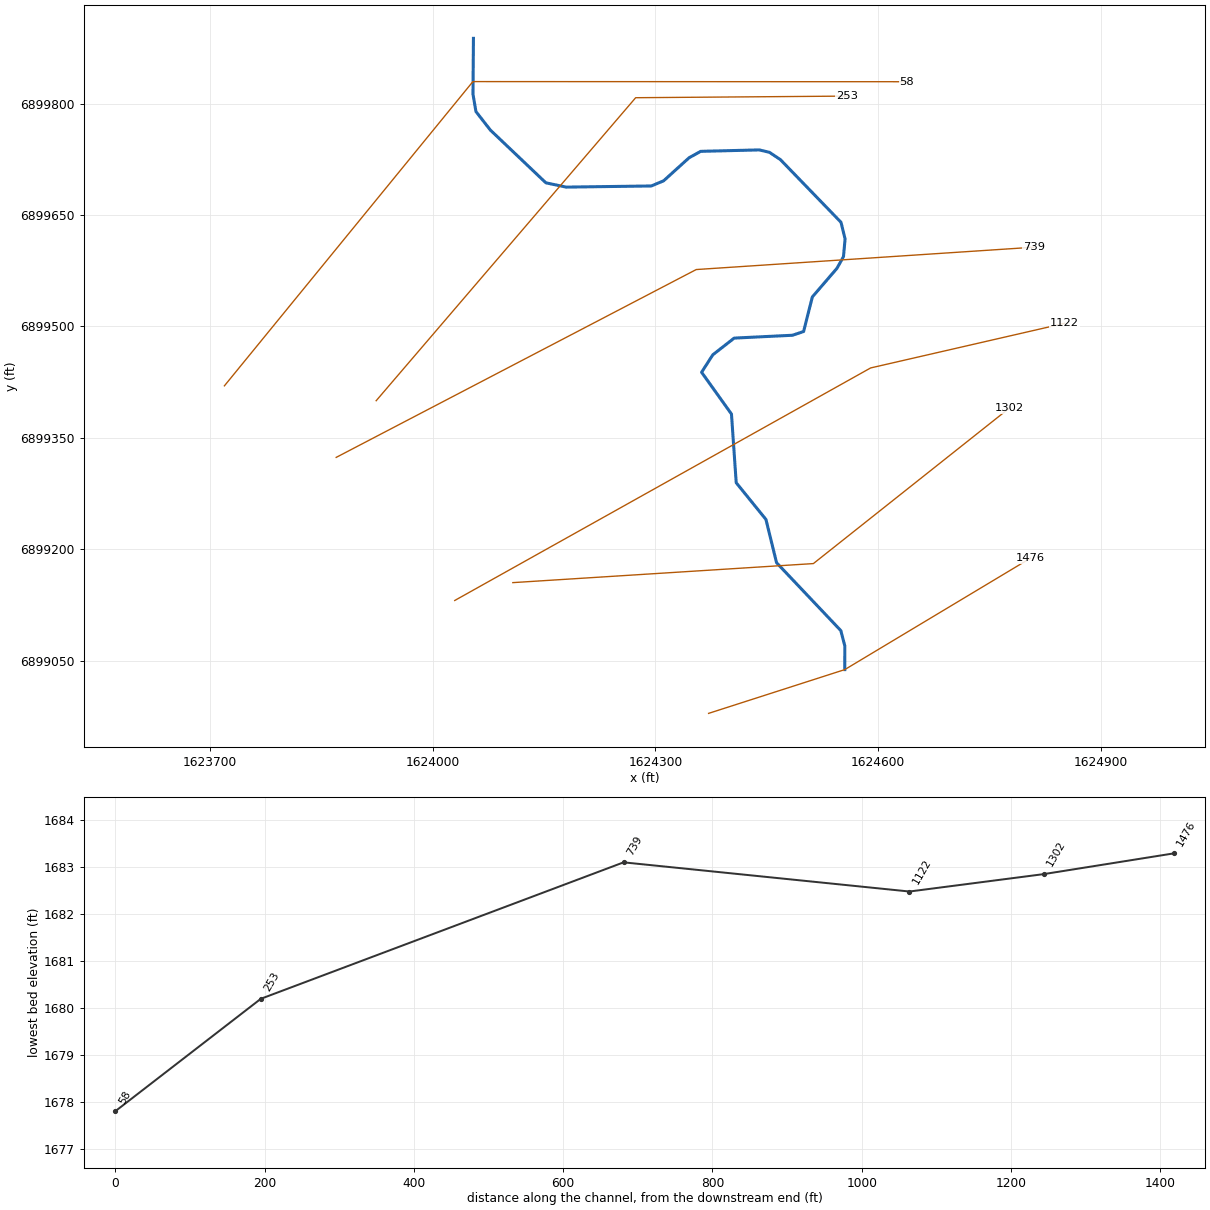
--- Deadman 50.prj (project) ---

Proj Title=Deadman 50 Base Level Engineering
Current Plan=p01
Default Exp/Contr=0.3,0.1
English Units
Geom File=g01
Flow File=f01
Plan File=p01
BEGIN DESCRIPTION:
Deadman 50
END DESCRIPTION:

--- Deadman 50.p01 (plan) ---

Plan Title=Multiple Run
Short Identifier=Multiple
Geom File=g01
Flow File=f01
Subcritical Flow
K Sum by GR= 0
Std Step Tol= 0.01
Critical Tol= 0.01
Num of Std Step Trials= 20
Max Error Tol= 0.3
Flow Tol Ratio= 0.001
Split Flow NTrial= 30
Split Flow Tol= 0.02
Split Flow Ratio= 0.02
Log Output Level= 0
Friction Slope Method= 1
Unsteady Friction Slope Method= 2
Unsteady Bridges Friction Slope Method= 1
Parabolic Critical Depth
Global Vel Dist=  1 , 1 , 1
Global Log Level= 0
CheckData=True
Encroach Param= -1, 0, 0, 0
BEGIN DESCRIPTION:
Multiple Run
END DESCRIPTION:

--- Deadman 50.f01 (steady flow) ---

Flow Title=Multiple
Number of Profiles=7
Profile Names=10-year,25-year,50-year,1pct_min,100-year,1pct_plu,500-year
River Rch & RM= Deadman 50,Reach-1,1476
     208     284     345     209     416     831     616
River Rch & RM= Deadman 50,Reach-1,1302
     215     294     357     217     432     863     641
Boundary for River Rch & Prof#=Deadman 50,Reach-1,1
Up Type=0
Dn Type=3
Dn Slope=0.009
Boundary for River Rch & Prof#=Deadman 50,Reach-1,2
Up Type=0
Dn Type=3
Dn Slope=0.009
Boundary for River Rch & Prof#=Deadman 50,Reach-1,3
Up Type=0
Dn Type=3
Dn Slope=0.009
Boundary for River Rch & Prof#=Deadman 50,Reach-1,4
Up Type=0
Dn Type=3
Dn Slope=0.009
Boundary for River Rch & Prof#=Deadman 50,Reach-1,5
Up Type=0
Dn Type=3
Dn Slope=0.009
Boundary for River Rch & Prof#=Deadman 50,Reach-1,6
Up Type=0
Dn Type=3
Dn Slope=0.009
Boundary for River Rch & Prof#=Deadman 50,Reach-1,7
Up Type=0
Dn Type=3
Dn Slope=0.009

--- Deadman 50.g01 (geometry) ---

Geom Title=Existing Conditions

River Reach=Deadman 50,Reach-1
Reach XY= 30
      1624555.00      6899038.00      1624555.07      6899069.88
      1624549.67      6899090.51      1624463.14      6899181.94
      1624448.86      6899240.17      1624408.82      6899289.59
      1624402.43      6899382.12      1624362.22      6899438.34
      1624377.26      6899461.84      1624406.09      6899484.36
      1624484.73      6899488.21      1624499.56      6899493.25
      1624511.34      6899539.80      1624544.53      6899578.40
      1624553.25      6899594.10      1624555.41      6899617.86
      1624549.92      6899640.31      1624468.34      6899724.67
      1624453.52      6899734.55      1624439.79      6899737.76
      1624360.98      6899735.84      1624345.37      6899727.19
      1624311.06      6899696.14      1624294.49      6899689.21
      1624179.88      6899687.68      1624152.53      6899693.45
      1624077.85      6899764.42      1624058.37      6899789.39
      1624054.40      6899812.75      1624055.00      6899888.00

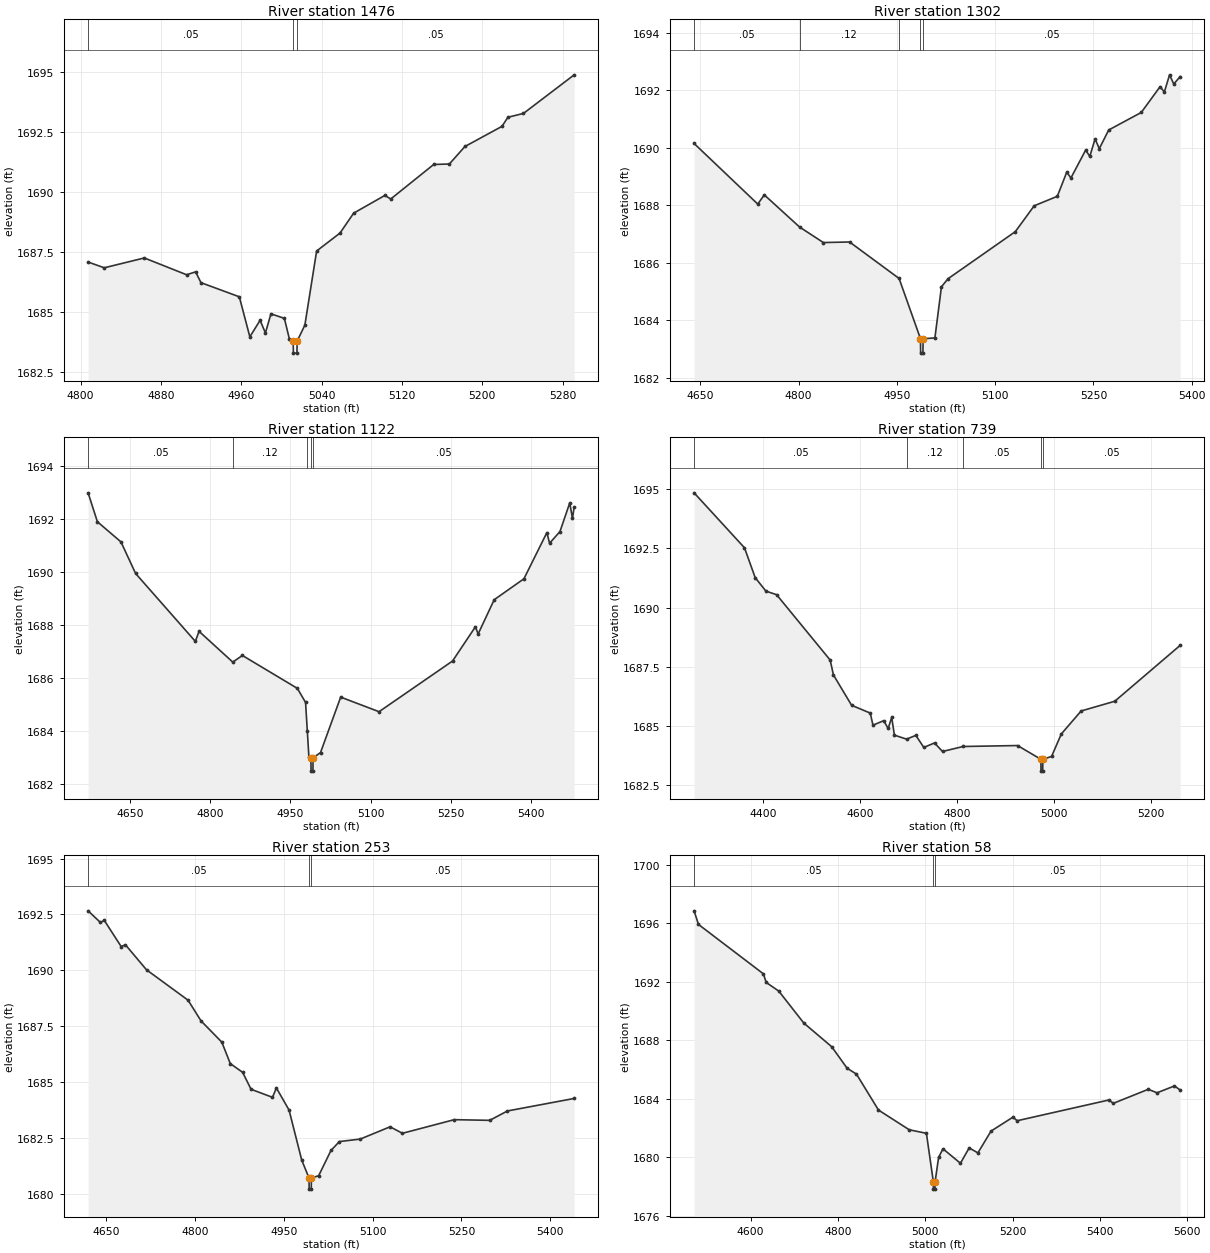
Type RM Length L Ch R = 1,1476,174,174,174
BEGIN DESCRIPTION:
Deadman 50 2.0
END DESCRIPTION:
XS GIS Cut Line= 3
      1624371.64      6898979.06      1624555.00      6899038.00
      1624804.96      6899187.98
#Sta/Elev= 30
  4807.4 1687.09  4823.5 1686.85  4863.4 1687.26  4905.5 1686.56  4914.5 1686.68
  4919.8 1686.23  4958.0 1685.64  4968.5 1683.97  4978.7 1684.66  4984.0 1684.13
  4989.5 1684.93  5002.9 1684.74  5007.8 1683.89  5011.6 1683.79  5011.9 1683.29
  5015.4 1683.29  5015.6 1683.79  5023.3 1684.46  5035.0 1687.55  5058.3 1688.30
  5071.9 1689.13  5103.0 1689.87  5108.8 1689.72  5151.6 1691.16  5167.2 1691.18
  5182.7 1691.91  5219.6 1692.75  5225.5 1693.13  5241.0 1693.29  5291.5 1694.90
#Mann=3,-1,0
  4807.4    0.05       0  5011.6    0.03       0  5015.6    0.05       0
Bank Sta=5011.6,5015.6
Exp/Cntr=0.3,0.1

Type RM Length L Ch R = 1,1302,180,180,180
BEGIN DESCRIPTION:
Mapping XS 3013b8bd
END DESCRIPTION:
XS GIS Cut Line= 3
      1624108.03      6899155.11      1624512.73      6899180.76
      1624776.50      6899390.00
#Sta/Elev= 30
  4640.3 1690.15  4737.5 1688.04  4747.5 1688.36  4801.4 1687.24  4837.7 1686.70
  4877.7 1686.72  4953.3 1685.45  4986.0 1683.35  4986.2 1682.85  4989.7 1682.85
  4990.0 1683.35  5008.0 1683.38  5018.0 1685.16  5028.0 1685.44  5130.8 1687.08
  5159.6 1687.98  5194.9 1688.31  5209.3 1689.15  5215.7 1688.95  5238.2 1689.92
  5244.5 1689.70  5252.6 1690.31  5259.0 1689.97  5273.4 1690.62  5323.1 1691.23
  5351.9 1692.13  5358.3 1691.94  5366.3 1692.54  5372.7 1692.22  5382.5 1692.48
#Mann=5,-1,0
  4640.3    0.05       0  4801.4    0.12       0  4953.3    0.05       0
  4986.0    0.03       0  4990.0    0.05       0
Bank Sta=4986,4990
Exp/Cntr=0.3,0.1

Type RM Length L Ch R = 1,1122,383,383,383
BEGIN DESCRIPTION:
Mapping XS 7d8e3354
END DESCRIPTION:
XS GIS Cut Line= 3
      1624029.83      6899131.07      1624589.82      6899444.19
      1624850.92      6899504.21
#Sta/Elev= 30
  4571.3 1692.97  4588.7 1691.88  4632.8 1691.12  4660.2 1689.93  4772.0 1687.37
  4778.9 1687.75  4842.0 1686.59  4860.0 1686.84  4962.8 1685.60  4978.2 1685.07
  4981.5 1683.99  4984.5 1683.00  4988.2 1682.98  4988.5 1682.48  4992.0 1682.48
  4992.2 1682.98  5006.2 1683.18  5043.9 1685.27  5115.7 1684.72  5253.2 1686.63
  5296.0 1687.92  5301.1 1687.65  5331.1 1688.94  5386.8 1689.73  5429.7 1691.47
  5434.8 1691.07  5454.2 1691.51  5472.5 1692.59  5477.6 1692.01  5480.8 1692.44
#Mann=5,-1,0
  4571.3    0.05       0  4842.0    0.12       0  4981.5    0.05       0
  4988.2    0.03       0  4992.2    0.05       0
Bank Sta=4988.2,4992.2
Exp/Cntr=0.3,0.1

Type RM Length L Ch R = 1,739,486,486,486
BEGIN DESCRIPTION:
Mapping XS 88453cca
END DESCRIPTION:
XS GIS Cut Line= 3
      1623870.21      6899323.74      1624354.98      6899576.67
      1624809.61      6899606.77
#Sta/Elev= 30
  4257.0 1694.85  4360.9 1692.53  4383.0 1691.27  4405.1 1690.70  4427.1 1690.55
  4537.6 1687.79  4544.4 1687.16  4581.8 1685.88  4620.3 1685.55  4625.9 1685.04
  4648.0 1685.23  4657.2 1684.90  4664.5 1685.37  4670.1 1684.62  4695.2 1684.45
  4714.3 1684.61  4730.7 1684.10  4752.8 1684.29  4769.3 1683.93  4811.8 1684.14
  4924.1 1684.18  4972.2 1683.60  4972.4 1683.10  4975.9 1683.10  4976.2 1683.60
  4994.2 1683.72  5014.3 1684.67  5055.2 1685.64  5124.5 1686.05  5259.4 1688.41
#Mann=5,-1,0
  4257.0    0.05       0  4695.2    0.12       0  4811.8    0.05       0
  4972.2    0.05       0  4976.2    0.05       0
Bank Sta=4972.2,4976.2
Exp/Cntr=0.3,0.1

Type RM Length L Ch R = 1,253,195,195,195
BEGIN DESCRIPTION:
Mapping XS 24b39594
END DESCRIPTION:
XS GIS Cut Line= 3
      1623924.05      6899400.07      1624273.44      6899808.05
      1624557.69      6899810.22
#Sta/Elev= 30
  4619.1 1692.66  4639.9 1692.14  4646.5 1692.23  4675.0 1691.06  4682.2 1691.14
  4717.8 1690.02  4788.0 1688.66  4810.0 1687.73  4845.1 1686.78  4859.4 1685.82
  4880.2 1685.43  4894.5 1684.67  4930.7 1684.31  4937.3 1684.73  4958.7 1683.74
  4980.1 1681.50  4992.4 1680.70  4992.7 1680.20  4996.2 1680.20  4996.4 1680.70
  5008.7 1680.80  5029.5 1681.93  5043.8 1682.33  5078.9 1682.44  5129.4 1682.99
  5150.3 1682.70  5237.8 1683.31  5297.8 1683.28  5327.8 1683.70  5440.5 1684.26
#Mann=3,-1,0
  4619.1    0.05       0  4992.4    0.05       0  4996.4    0.05       0
Bank Sta=4992.4,4996.4
Exp/Cntr=0.3,0.1

Type RM Length L Ch R = 1,58,0,0,0
BEGIN DESCRIPTION:
Deadman 50 1.0
END DESCRIPTION:
XS GIS Cut Line= 3
      1623719.69      6899420.10      1624054.26      6899829.75
      1624638.04      6899829.58
#Sta/Elev= 30
  4470.8 1696.85  4480.8 1695.92  4629.4 1692.54  4635.9 1691.95  4664.6 1691.36
  4722.0 1689.17  4785.9 1687.55  4821.1 1686.08  4842.5 1685.68  4892.9 1683.22
  4963.3 1681.87  5002.6 1681.63  5018.5 1678.31  5018.7 1677.81  5022.2 1677.81
  5022.5 1678.31  5030.5 1679.98  5040.5 1680.57  5080.5 1679.58  5100.5 1680.63
  5120.5 1680.29  5150.5 1681.78  5200.5 1682.73  5210.5 1682.49  5420.5 1683.91
  5430.5 1683.68  5510.5 1684.64  5530.5 1684.40  5570.5 1684.87  5583.5 1684.59
#Mann=3,-1,0
  4470.8    0.05       0  5018.5    0.03       0  5022.5    0.05       0
Bank Sta=5018.5,5022.5
Exp/Cntr=0.3,0.1

Chan Stop Cuts=-1