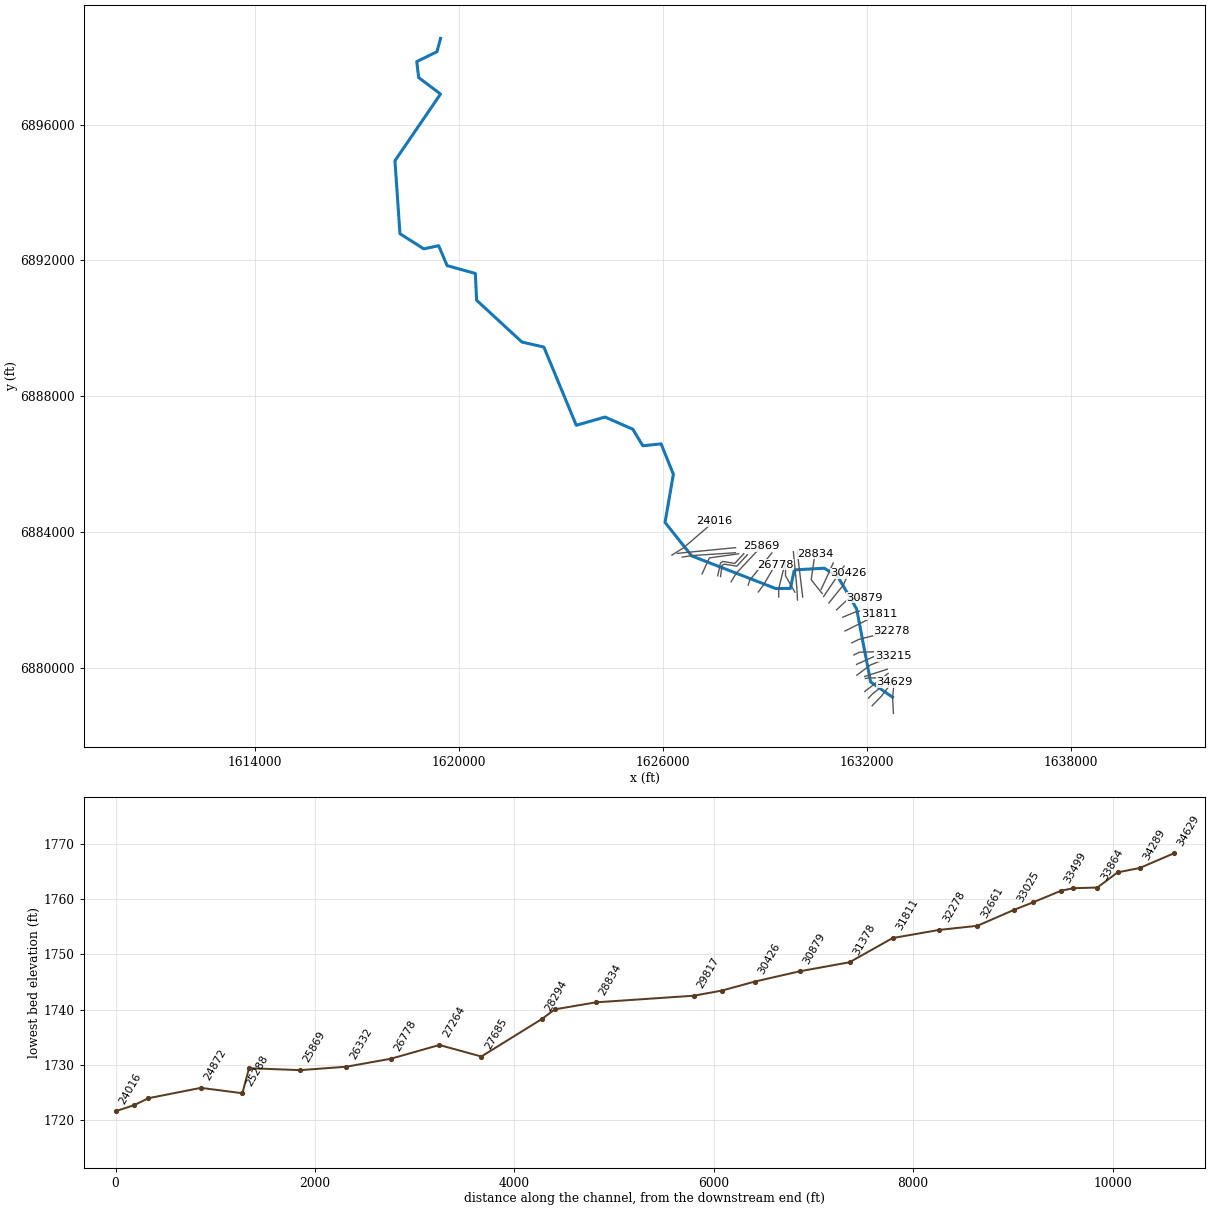
--- Deadman 53.prj (project) ---

Proj Title=Deadman 53 Base Level Engineering
Current Plan=p01
Default Exp/Contr=0.3,0.1
English Units
Geom File=g01
Flow File=f01
Plan File=p01
Y Axis Title=Elevation
X Axis Title(PF)=Main Channel Distance
X Axis Title(XS)=Station
BEGIN DESCRIPTION:
Deadman 53
END DESCRIPTION:
DSS Export Rating Curves= 0
DSS Export Rating Curve Sorted= 0
DSS Export Volume Flow Curves= 0
DXF OffsetX= 0
DXF OffsetY= 0
DXF ScaleX= 1
DXF ScaleY= 10

--- Deadman 53.p01 (plan) ---

Plan Title=Multiple Run
Short Identifier=Multiple
Geom File=g01
Flow File=f01
Subcritical Flow
K Sum by GR= 0
Std Step Tol= 0.01
Critical Tol= 0.01
Num of Std Step Trials= 20
Max Error Tol= 0.3
Flow Tol Ratio= 0.001
Split Flow NTrial= 30
Split Flow Tol= 0.02
Split Flow Ratio= 0.02
Log Output Level= 0
Friction Slope Method= 1
Unsteady Friction Slope Method= 2
Unsteady Bridges Friction Slope Method= 1
Parabolic Critical Depth
Global Vel Dist=  1 , 1 , 1
Global Log Level= 0
CheckData=True
Encroach Param= -1, 0, 0, 0
BEGIN DESCRIPTION:
Multiple Run
END DESCRIPTION:

--- Deadman 53.f01 (steady flow) ---

Flow Title=Multiple
Program Version=4.10
Number of Profiles= 7
Profile Names=10-year,25-year,50-year,1pct_min,100-year,1pct_plu,500-year
River Rch & RM=Deadman 53,Reach-1         ,34629
     238     328     402     245     489     976     734
River Rch & RM=Deadman 53,Reach-1         ,34289
     275     382     470     288     575    1147     871
River Rch & RM=Deadman 53,Reach-1         ,30426
     400     566     707     438     875    1745    1358
River Rch & RM=Deadman 53,Reach-1         ,28421
     473     672     840     521    1041    2076    1619
River Rch & RM=Deadman 53,Reach-1         ,22164
     515     735     921     573    1144    2282    1789
River Rch & RM=Deadman 53,Reach-1         ,20326
     646     930    1173     735    1466    2925    2320
River Rch & RM=Deadman 53,Reach-1         ,16708
     726    1050    1329     834    1665    3322    2649
River Rch & RM=Deadman 53,Reach-1         ,15307
     861    1251    1588    1000    1994    3979    3189
River Rch & RM=Deadman 53,Reach-1         ,9082
     918    1336    1698    1069    2134    4257    3416
River Rch & RM=Deadman 53,Reach-1         ,7696
     931    1351    1714    1077    2149    4287    3425
Boundary for River Rch & Prof#=Deadman 53,Reach-1         , 1
Up Type= 0
Dn Type= 3
Dn Slope=0.0009
Boundary for River Rch & Prof#=Deadman 53,Reach-1         , 2
Up Type= 0
Dn Type= 3
Dn Slope=0.0009
Boundary for River Rch & Prof#=Deadman 53,Reach-1         , 3
Up Type= 0
Dn Type= 3
Dn Slope=0.0009
Boundary for River Rch & Prof#=Deadman 53,Reach-1         , 4
Up Type= 0
Dn Type= 3
Dn Slope=0.0009
Boundary for River Rch & Prof#=Deadman 53,Reach-1         , 5
Up Type= 0
Dn Type= 3
Dn Slope=0.0009
Boundary for River Rch & Prof#=Deadman 53,Reach-1         , 6
Up Type= 0
Dn Type= 3
Dn Slope=0.0009
Boundary for River Rch & Prof#=Deadman 53,Reach-1         , 7
Up Type= 0
Dn Type= 3
Dn Slope=0.0009
DSS Import GetInterval= 0
DSS Import GetPeak= 0
DSS Import FillOption= 0

--- Deadman 53.g01 (geometry) ---

Geom Title=Existing Conditions

River Reach=Deadman 53,Reach-1
Reach XY= 30
      1632755.00      6879138.00      1632108.67      6879589.58
      1631696.96      6881741.32      1631146.50      6882684.45
      1630744.33      6882936.97      1629865.28      6882887.02
      1629749.56      6882343.18      1629315.44      6882339.06
      1626845.32      6883298.78      1626060.71      6884285.65
      1626305.49      6885703.20      1625944.95      6886597.98
      1625406.55      6886541.75      1625115.18      6887027.68
      1624294.67      6887387.13      1623448.66      6887145.36
      1622494.63      6889448.13      1621848.66      6889596.03
      1620515.32      6890827.83      1620479.09      6891615.15
      1619648.83      6891845.86      1619399.59      6892432.83
      1618960.97      6892340.14      1618260.47      6892785.55
      1618113.04      6894934.69      1619454.52      6896898.49
      1618812.69      6897381.52      1618754.56      6897853.18
      1619349.59      6898143.17      1619455.00      6898538.00

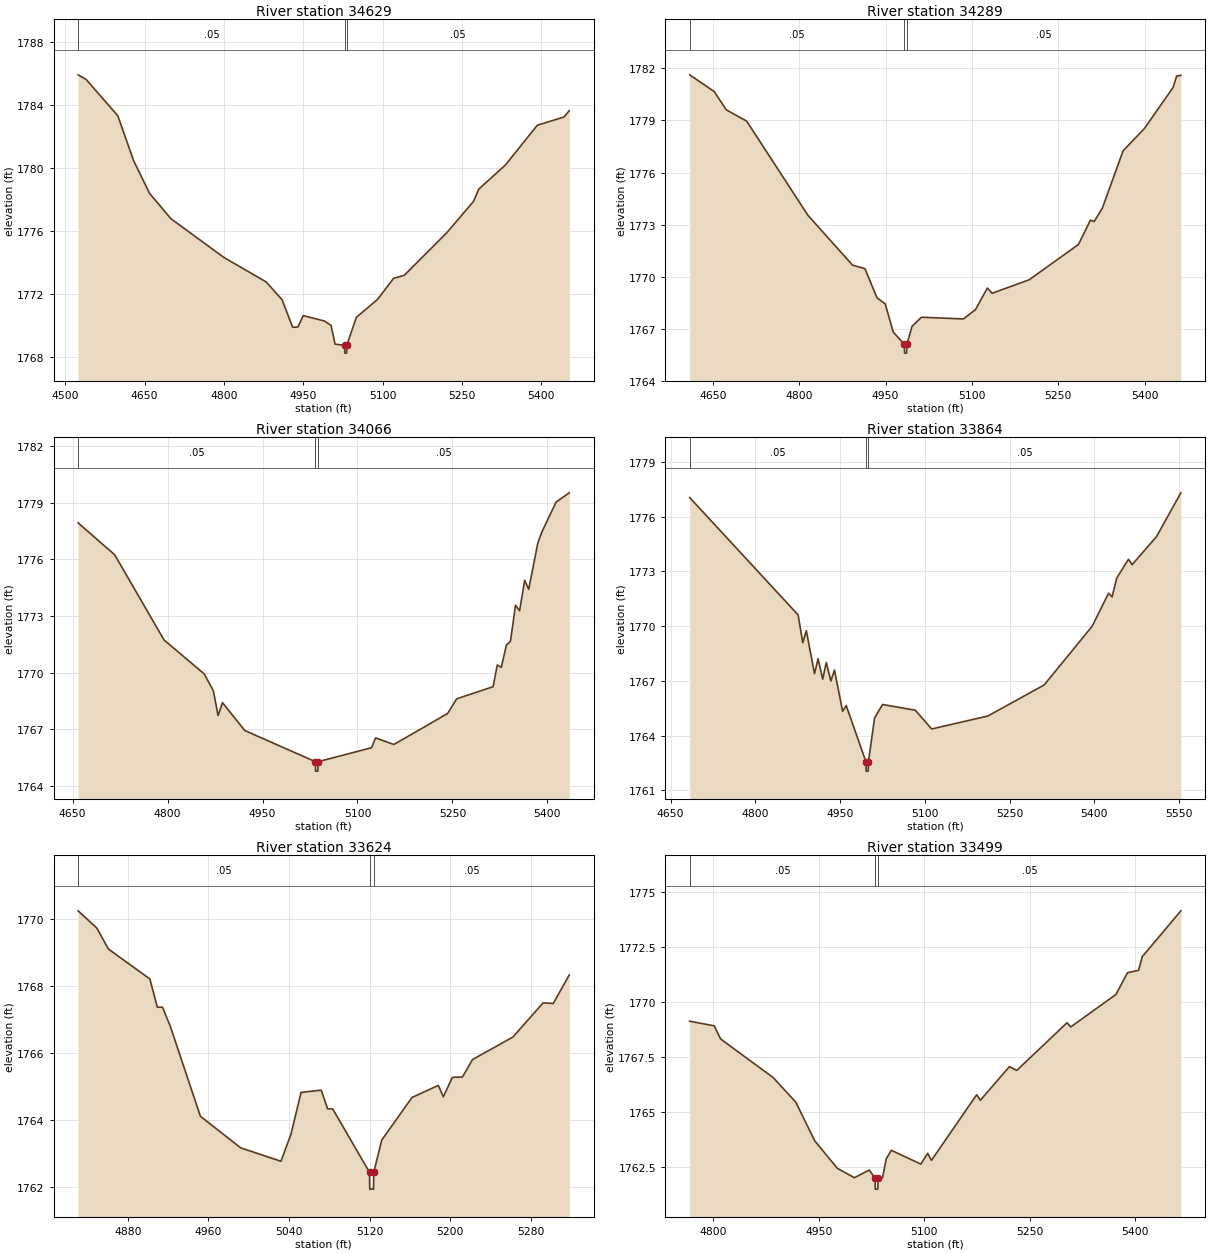
Type RM Length L Ch R = 1,34629,340,340,340
BEGIN DESCRIPTION:
Deadman 53 52.0
END DESCRIPTION:
XS GIS Cut Line= 3
      1632780.00      6878662.96      1632755.00      6879138.00
      1632805.00      6879588.03
#Sta/Elev= 30
  4524.3 1785.89  4539.4 1785.60  4599.4 1783.29  4629.5 1780.42  4659.5 1778.36
  4699.6 1776.76  4799.7 1774.30  4879.8 1772.74  4909.9 1771.61  4929.9 1769.86
  4939.9 1769.88  4949.9 1770.60  4990.0 1770.26  5002.5 1769.98  5010.1 1768.79
  5028.1 1768.72  5028.4 1768.22  5032.0 1768.22  5032.2 1768.72  5050.3 1770.49
  5090.6 1771.64  5120.7 1772.97  5140.9 1773.16  5221.4 1775.87  5271.7 1777.85
  5281.7 1778.63  5332.0 1780.16  5392.4 1782.69  5442.7 1783.21  5452.8 1783.61
#Mann=3,-1,0
  4524.3    0.05       0  5028.1    0.05       0  5032.2    0.05       0
Bank Sta=5028.1,5032.2
Exp/Cntr=0.3,0.1

Type RM Length L Ch R = 1,34289,223,223,223
BEGIN DESCRIPTION:
Deadman 53 51.0
END DESCRIPTION:
XS GIS Cut Line= 3
      1632154.97      6878887.97      1632425.72      6879168.81
      1632704.98      6879537.98
#Sta/Elev= 30
  4609.9 1781.63  4652.3 1780.67  4673.6 1779.61  4708.9 1778.96  4815.1 1773.54
  4892.8 1770.66  4914.2 1770.46  4935.2 1768.78  4949.4 1768.43  4963.5 1766.80
  4982.8 1766.09  4983.1 1765.59  4986.7 1765.59  4987.0 1766.09  4996.0 1767.13
  5012.4 1767.66  5085.2 1767.56  5106.1 1768.09  5126.9 1769.34  5135.2 1769.04
  5199.6 1769.82  5285.0 1771.85  5305.8 1773.25  5312.5 1773.18  5326.7 1773.96
  5362.6 1777.25  5399.4 1778.53  5449.4 1780.90  5455.6 1781.56  5462.9 1781.60
#Mann=3,-1,0
  4609.9    0.05       0  4982.8    0.03       0  4987.0    0.05       0
Bank Sta=4982.8,4987
Exp/Cntr=0.3,0.1

Type RM Length L Ch R = 1,34066,202,202,202
BEGIN DESCRIPTION:
Mapping XS 9a44ffad
END DESCRIPTION:
XS GIS Cut Line= 3
      1632047.11      6879114.01      1632166.89      6879238.23
      1632639.31      6879613.51
#Sta/Elev= 30
  4658.7 1777.94  4716.7 1776.24  4794.4 1771.74  4857.9 1769.94  4872.3 1769.05
  4879.9 1767.73  4886.7 1768.42  4922.0 1766.94  5033.6 1765.29  5033.9 1764.79
  5037.5 1764.79  5037.8 1765.29  5122.3 1766.03  5128.6 1766.55  5157.5 1766.20
  5242.4 1767.84  5256.8 1768.62  5314.2 1769.26  5320.9 1770.41  5327.3 1770.29
  5335.3 1771.47  5341.7 1771.66  5349.7 1773.58  5356.1 1773.28  5364.2 1774.90
  5370.5 1774.42  5385.0 1776.88  5391.4 1777.46  5413.8 1779.04  5434.6 1779.53
#Mann=3,-1,0
  4658.7    0.05       0  5033.6    0.03       0  5037.8    0.05       0
Bank Sta=5033.6,5037.8
Exp/Cntr=0.3,0.1

Type RM Length L Ch R = 1,33864,240,240,240
BEGIN DESCRIPTION:
Mapping XS fb67b1e9
END DESCRIPTION:
XS GIS Cut Line= 2
      1631936.19      6879306.97      1632623.80      6879839.32
#Sta/Elev= 30
  4683.7 1777.05  4875.7 1770.62  4883.9 1769.10  4890.2 1769.76  4904.7 1767.40
  4911.0 1768.22  4919.2 1767.10  4925.5 1768.01  4933.7 1767.00  4940.0 1767.60
  4954.5 1765.34  4960.8 1765.65  4995.9 1762.56  4996.1 1762.06  4999.8 1762.06
  5000.1 1762.56  5011.0 1764.97  5025.1 1765.71  5083.1 1765.40  5112.1 1764.37
  5211.6 1765.08  5311.2 1766.78  5396.3 1770.00  5425.3 1771.81  5431.6 1771.61
  5439.8 1772.64  5460.6 1773.67  5467.0 1773.37  5510.4 1774.92  5553.3 1777.31
#Mann=3,-1,0
  4683.7    0.05       0  4995.9    0.03       0  5000.1    0.05       0
Bank Sta=4995.9,5000.1
Exp/Cntr=0.3,0.1

Type RM Length L Ch R = 1,33624,125,125,125
BEGIN DESCRIPTION:
Mapping XS 1947cb8b
END DESCRIPTION:
XS GIS Cut Line= 4
      1631955.63      6879687.98      1632034.64      6879706.36
      1632202.79      6879705.44      1632440.85      6879721.92
#Sta/Elev= 30
  4830.5 1770.23  4849.0 1769.72  4860.7 1769.09  4901.8 1768.20  4909.2 1767.36
  4914.3 1767.36  4922.0 1766.80  4952.0 1764.11  4992.0 1763.17  5032.0 1762.77
  5042.0 1763.58  5052.0 1764.82  5072.0 1764.89  5078.4 1764.33  5083.4 1764.33
  5120.0 1762.44  5120.2 1761.94  5123.9 1761.94  5124.2 1762.44  5132.1 1763.40
  5162.2 1764.67  5188.3 1765.03  5193.3 1764.69  5202.3 1765.27  5212.3 1765.28
  5222.3 1765.80  5262.4 1766.47  5292.5 1767.49  5302.5 1767.47  5318.4 1768.32
#Mann=3,-1,0
  4830.5    0.05       0  5120.0    0.03       0  5124.2    0.05       0
Bank Sta=5120,5124.2
Exp/Cntr=0.3,0.1

Type RM Length L Ch R = 1,33499,284,284,284
BEGIN DESCRIPTION:
Mapping XS ce1a904a
END DESCRIPTION:
XS GIS Cut Line= 2
      1631931.80      6879748.40      1632597.26      6879961.35
#Sta/Elev= 30
  4766.2 1769.13  4801.1 1768.92  4810.2 1768.32  4885.1 1766.56  4917.2 1765.44
  4944.1 1763.68  4976.2 1762.43  5000.6 1762.00  5021.6 1762.35  5030.0 1761.98
  5030.2 1761.48  5033.9 1761.48  5034.2 1761.98  5040.5 1762.00  5045.8 1762.86
  5053.0 1763.25  5095.0 1762.62  5104.8 1763.11  5110.1 1762.79  5174.4 1765.78
  5179.7 1765.53  5221.0 1767.06  5231.5 1766.89  5303.0 1769.06  5308.3 1768.87
  5372.6 1770.35  5389.0 1771.34  5404.7 1771.45  5410.0 1772.07  5464.9 1774.16
#Mann=3,-1,0
  4766.2    0.05       0  5030.0    0.05       0  5034.2    0.05       0
Bank Sta=5030,5034.2
Exp/Cntr=0.3,0.1

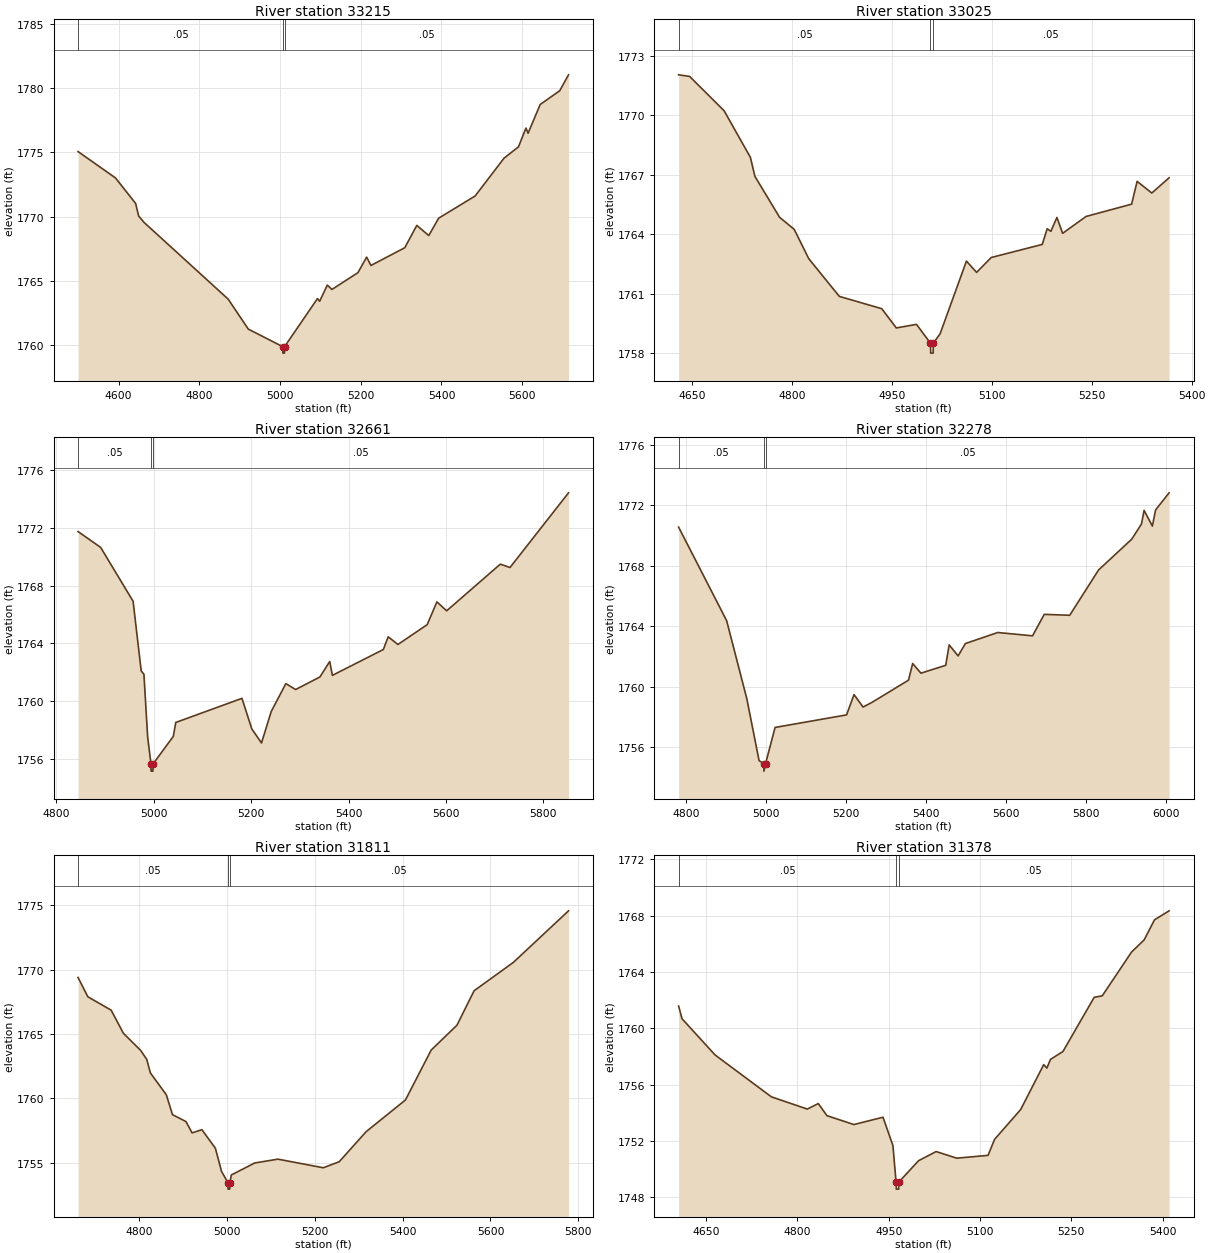
Type RM Length L Ch R = 1,33215,190,190,190
BEGIN DESCRIPTION:
Deadman 53 49.0
END DESCRIPTION:
XS GIS Cut Line= 3
      1631704.98      6879787.99      1632105.00      6880088.00
      1632770.27      6880351.02
#Sta/Elev= 30
  4499.5 1775.06  4592.2 1773.01  4642.2 1771.02  4649.5 1770.05  4663.1 1769.54
  4871.4 1763.57  4921.4 1761.23  5006.9 1759.86  5007.2 1759.36  5010.9 1759.36
  5011.2 1759.86  5092.8 1763.61  5098.2 1763.40  5117.2 1764.66  5128.6 1764.32
  5193.1 1765.63  5214.6 1766.84  5225.3 1766.19  5309.1 1767.57  5338.9 1769.31
  5368.6 1768.52  5393.0 1769.87  5483.4 1771.60  5555.2 1774.55  5590.9 1775.43
  5609.3 1776.89  5614.7 1776.49  5644.7 1778.73  5693.1 1779.80  5714.9 1781.04
#Mann=3,-1,0
  4499.5    0.05       0  5006.9    0.03       0  5011.2    0.05       0
Bank Sta=5006.9,5011.2
Exp/Cntr=0.3,0.1

Type RM Length L Ch R = 1,33025,364,364,364
BEGIN DESCRIPTION:
Mapping XS 3d02d113
END DESCRIPTION:
XS GIS Cut Line= 2
      1631696.65      6880105.51      1632368.76      6880407.18
#Sta/Elev= 30
  4629.4 1772.04  4645.9 1771.96  4697.7 1770.23  4737.2 1767.88  4744.0 1766.92
  4781.0 1764.86  4803.0 1764.25  4824.9 1762.77  4870.8 1760.87  4934.5 1760.25
  4956.4 1759.28  4986.7 1759.46  5007.7 1758.51  5008.0 1758.01  5011.7 1758.01
  5012.0 1758.51  5022.2 1758.99  5061.7 1762.65  5077.0 1762.08  5098.9 1762.83
  5175.6 1763.49  5183.0 1764.28  5188.5 1764.15  5197.6 1764.85  5206.2 1764.05
  5241.4 1764.90  5309.8 1765.52  5318.1 1766.67  5340.1 1766.08  5366.1 1766.85
#Mann=3,-1,0
  4629.4    0.05       0  5007.7    0.03       0  5012.0    0.05       0
Bank Sta=5007.7,5012
Exp/Cntr=0.3,0.1

Type RM Length L Ch R = 1,32661,383,383,383
BEGIN DESCRIPTION:
Deadman 53 48.0
END DESCRIPTION:
XS GIS Cut Line= 3
      1631617.76      6880382.38      1631774.03      6880462.25
      1632605.04      6880488.00
#Sta/Elev= 30
  4844.8 1771.74  4891.2 1770.64  4957.8 1766.91  4974.4 1762.09  4980.0 1761.86
  4987.7 1757.50  4994.5 1755.65  4994.7 1755.15  4998.5 1755.15  4998.8 1755.65
  5040.4 1757.56  5045.4 1758.52  5181.3 1760.19  5201.4 1758.08  5221.4 1757.10
  5241.4 1759.28  5271.4 1761.21  5291.4 1760.80  5341.4 1761.67  5361.4 1762.74
  5366.9 1761.78  5471.5 1763.57  5481.5 1764.45  5501.5 1763.92  5561.5 1765.29
  5581.5 1766.87  5601.5 1766.25  5711.6 1769.48  5731.6 1769.25  5851.7 1774.42
#Mann=3,-1,0
  4844.8    0.05       0  4994.5    0.05       0  4998.8    0.05       0
Bank Sta=4994.5,4998.8
Exp/Cntr=0.3,0.1

Type RM Length L Ch R = 1,32278,467,467,467
BEGIN DESCRIPTION:
Deadman 53 47.0
END DESCRIPTION:
XS GIS Cut Line= 3
      1631555.04      6880738.02      1631755.00      6880838.00
      1632725.47      6881090.73
#Sta/Elev= 30
  4782.1 1770.55  4902.2 1764.36  4952.6 1759.20  4983.3 1755.10  4995.1 1754.91
  4995.4 1754.41  4999.5 1754.91  5023.3 1757.30  5202.0 1758.13  5220.7 1759.47
  5243.3 1758.65  5266.4 1758.97  5357.0 1760.43  5367.3 1761.53  5388.0 1760.89
  5450.0 1761.41  5458.6 1762.76  5481.0 1762.03  5499.1 1762.85  5580.1 1763.58
  5667.0 1763.36  5696.4 1764.78  5760.0 1764.72  5832.3 1767.72  5915.0 1769.75
  5939.5 1770.76  5946.0 1771.66  5966.7 1770.62  5974.8 1771.69  6008.5 1772.82
#Mann=3,-1,0
  4782.1    0.05       0  4995.1    0.03       0  4999.5    0.05       0
Bank Sta=4995.1,4999.5
Exp/Cntr=0.3,0.1

Type RM Length L Ch R = 1,31811,433,433,433
BEGIN DESCRIPTION:
Deadman 53 46.0
END DESCRIPTION:
XS GIS Cut Line= 3
      1631355.02      6881088.01      1631655.00      6881238.00
      1632354.99      6881587.99
#Sta/Elev= 30
  4660.0 1769.39  4682.3 1767.89  4735.4 1766.85  4763.4 1765.05  4802.5 1763.73
  4816.5 1763.03  4824.9 1761.97  4861.2 1760.27  4875.2 1758.73  4906.0 1758.19
  4919.9 1757.31  4942.3 1757.56  4973.0 1756.12  4987.0 1754.32  5001.6 1753.44
  5001.9 1752.94  5005.7 1752.94  5006.0 1753.44  5009.4 1754.04  5062.5 1754.97
  5115.6 1755.27  5219.0 1754.60  5255.3 1755.07  5316.8 1757.41  5406.3 1759.87
  5465.0 1763.75  5523.7 1765.68  5562.8 1768.36  5652.2 1770.56  5778.0 1774.57
#Mann=3,-1,0
  4660.0    0.05       0  5001.6    0.03       0  5006.0    0.05       0
Bank Sta=5001.6,5006
Exp/Cntr=0.3,0.1

Type RM Length L Ch R = 1,31378,499,499,499
BEGIN DESCRIPTION:
Deadman 53 45.0
END DESCRIPTION:
XS GIS Cut Line= 3
      1631289.79      6881494.32      1631657.80      6881647.08
      1632054.97      6881737.99
#Sta/Elev= 30
  4604.8 1761.58  4610.4 1760.68  4664.6 1758.11  4757.2 1755.13  4816.2 1754.26
  4834.3 1754.65  4848.6 1753.79  4892.8 1753.16  4940.6 1753.68  4956.9 1751.67
  4962.1 1749.07  4962.5 1748.57  4966.4 1748.57  4966.7 1749.07  4999.0 1750.59
  5027.9 1751.24  5061.9 1750.77  5113.2 1750.97  5124.0 1752.11  5166.9 1754.23
  5204.7 1757.42  5209.9 1757.17  5215.8 1757.79  5236.3 1758.35  5287.6 1762.20
  5300.9 1762.31  5349.2 1765.43  5369.7 1766.28  5386.7 1767.71  5410.7 1768.35
#Mann=3,-1,0
  4604.8    0.05       0  4962.1    0.03       0  4966.7    0.05       0
Bank Sta=4962.1,4966.7
Exp/Cntr=0.3,0.1

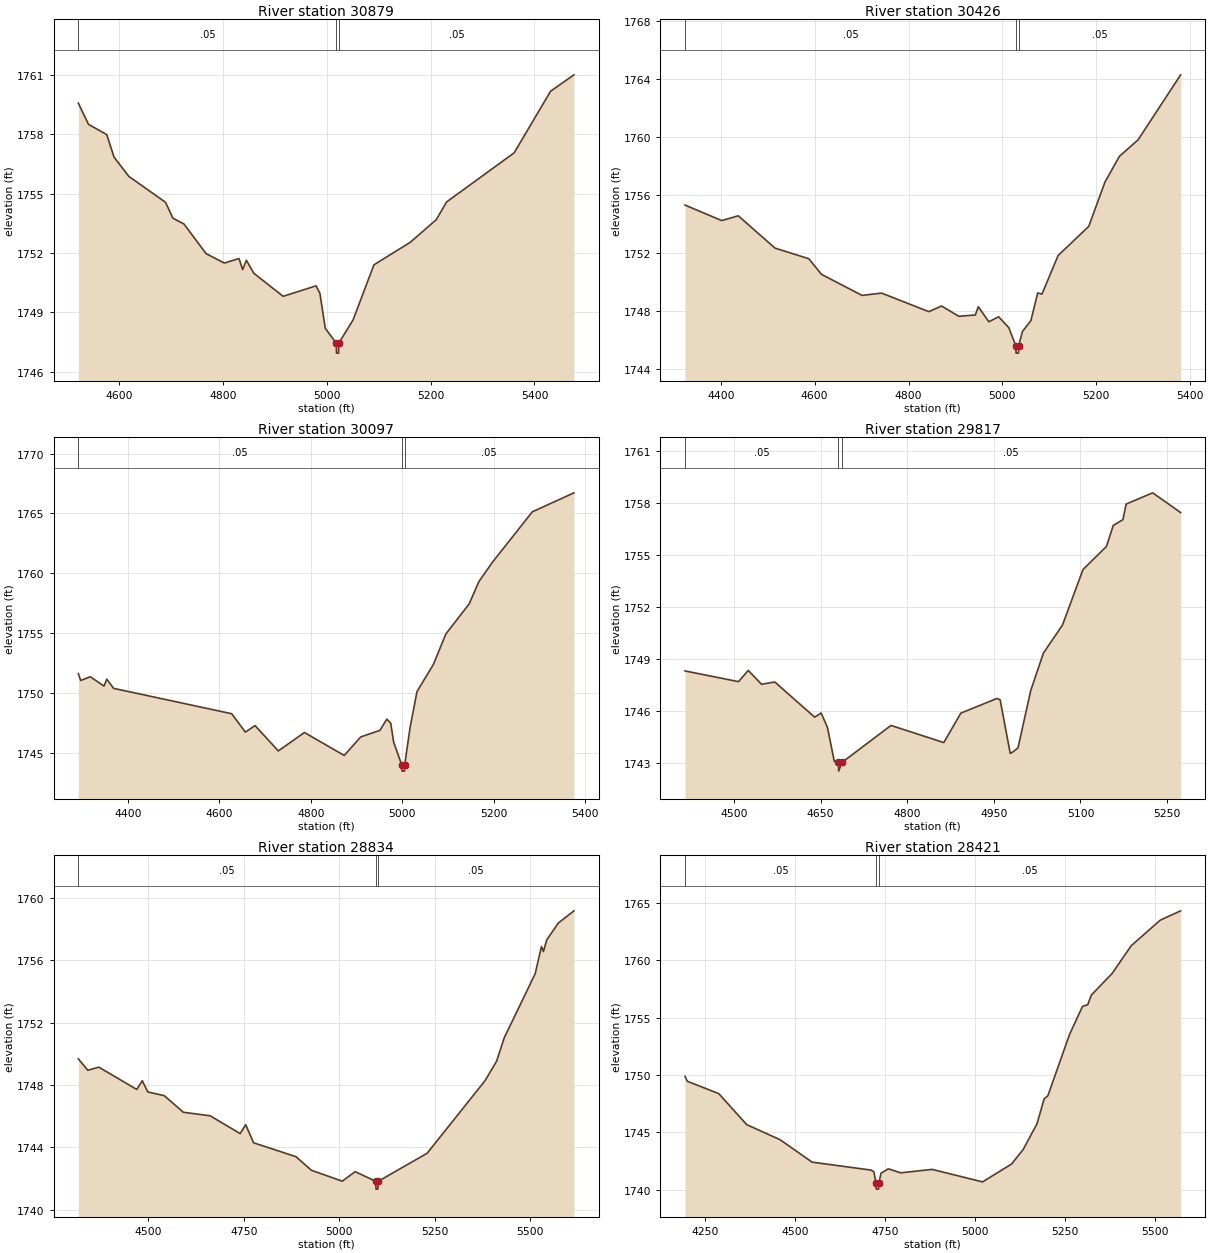
Type RM Length L Ch R = 1,30879,453,453,453
BEGIN DESCRIPTION:
Deadman 53 44.0
END DESCRIPTION:
XS GIS Cut Line= 3
      1631105.72      6881709.58      1631455.00      6882038.00
      1631930.01      6882063.00
#Sta/Elev= 30
  4521.0 1759.57  4540.6 1758.50  4575.8 1757.98  4589.9 1756.84  4618.3 1755.87
  4689.1 1754.56  4703.2 1753.76  4724.7 1753.46  4767.1 1751.97  4802.4 1751.49
  4830.7 1751.72  4837.6 1751.16  4844.9 1751.63  4859.0 1750.98  4915.7 1749.81
  4979.2 1750.34  4986.5 1749.96  4997.0 1748.19  5018.2 1747.44  5018.5 1746.94
  5022.5 1746.94  5022.8 1747.44  5050.5 1748.62  5090.6 1751.40  5160.7 1752.54
  5210.7 1753.68  5230.8 1754.58  5360.9 1757.06  5431.0 1760.17  5476.1 1761.00
#Mann=3,-1,0
  4521.0    0.05       0  5018.2    0.03       0  5022.8    0.05       0
Bank Sta=5018.2,5022.8
Exp/Cntr=0.3,0.1

Type RM Length L Ch R = 1,30426,329,329,329
BEGIN DESCRIPTION:
Deadman 53 43.0
END DESCRIPTION:
XS GIS Cut Line= 3
      1630880.00      6881913.00      1631305.00      6882438.00
      1631454.98      6882787.95
#Sta/Elev= 30
  4323.7 1755.28  4402.0 1754.21  4437.2 1754.54  4515.6 1752.31  4587.5 1751.58
  4614.7 1750.50  4701.0 1749.05  4742.6 1749.21  4843.3 1747.93  4870.5 1748.32
  4907.2 1747.61  4942.4 1747.70  4948.8 1748.27  4971.2 1747.23  4992.0 1747.58
  5013.7 1746.83  5028.7 1745.57  5029.2 1745.07  5034.3 1745.07  5034.8 1745.57
  5042.7 1746.56  5060.8 1747.31  5075.3 1749.22  5084.4 1749.14  5118.8 1751.80
  5184.1 1753.81  5218.6 1756.86  5249.4 1758.64  5289.3 1759.78  5379.9 1764.26
#Mann=3,-1,0
  4323.7    0.05       0  5028.7    0.03       0  5034.8    0.05       0
Bank Sta=5028.7,5034.8
Exp/Cntr=0.3,0.1

Type RM Length L Ch R = 1,30097,280,280,280
BEGIN DESCRIPTION:
Mapping XS c7f096ed
END DESCRIPTION:
XS GIS Cut Line= 2
      1630725.43      6882101.16      1631329.60      6883000.46
#Sta/Elev= 30
  4291.7 1751.60  4296.9 1751.03  4317.9 1751.34  4347.9 1750.56  4353.9 1751.14
  4368.9 1750.37  4627.0 1748.25  4656.9 1746.71  4677.9 1747.26  4728.9 1745.14
  4786.0 1746.68  4872.9 1744.76  4909.0 1746.31  4951.0 1746.86  4966.0 1747.80
  4974.6 1747.45  4981.0 1745.87  4998.9 1743.95  4999.4 1743.45  5004.5 1743.45
  5005.0 1743.95  5017.0 1747.12  5032.0 1750.10  5068.0 1752.38  5095.1 1754.92
  5146.0 1757.43  5167.3 1759.30  5197.0 1760.92  5284.0 1765.13  5375.1 1766.72
#Mann=3,-1,0
  4291.7    0.05       0  4998.9    0.03       0  5005.0    0.05       0
Bank Sta=4998.9,5005
Exp/Cntr=0.3,0.1

Type RM Length L Ch R = 1,29817,983,983,983
BEGIN DESCRIPTION:
Mapping XS 5621635f
END DESCRIPTION:
XS GIS Cut Line= 2
      1630654.31      6882313.71      1631011.53      6883094.04
#Sta/Elev= 30
  4415.2 1748.32  4507.9 1747.70  4524.7 1748.35  4547.7 1747.55  4570.7 1747.68
  4639.7 1745.65  4650.9 1745.89  4661.9 1745.05  4673.7 1743.10  4680.8 1743.03
  4681.3 1742.53  4686.9 1743.03  4771.9 1745.17  4863.3 1744.18  4892.8 1745.88
  4955.4 1746.73  4960.9 1746.65  4978.4 1743.55  4983.9 1743.66  4991.8 1743.87
  5013.8 1747.18  5035.8 1749.35  5068.8 1750.97  5104.4 1754.18  5144.9 1755.51
  5156.8 1756.73  5173.5 1757.06  5179.0 1757.96  5225.0 1758.61  5273.4 1757.47
#Mann=3,-1,0
  4415.2    0.05       0  4680.8    0.03       0  4686.9    0.05       0
Bank Sta=4680.8,4686.9
Exp/Cntr=0.3,0.1

Type RM Length L Ch R = 1,28834,413,413,413
BEGIN DESCRIPTION:
Mapping XS 4a0c6ca7
END DESCRIPTION:
XS GIS Cut Line= 3
      1630683.78      6882191.38      1630360.84      6882597.67
      1630471.95      6883368.50
#Sta/Elev= 30
  4316.5 1749.68  4341.4 1748.95  4370.2 1749.15  4469.5 1747.72  4484.0 1748.28
  4498.4 1747.56  4541.7 1747.32  4591.3 1746.26  4661.8 1746.03  4740.3 1744.89
  4754.7 1745.46  4775.5 1744.30  4886.4 1743.41  4926.8 1742.54  5007.6 1741.84
  5041.4 1742.45  5095.5 1741.83  5096.0 1741.33  5101.1 1741.33  5101.6 1741.83
  5229.9 1743.63  5381.4 1748.28  5411.7 1749.53  5431.9 1751.04  5512.8 1755.14
  5529.2 1756.88  5534.3 1756.56  5543.1 1757.31  5573.4 1758.39  5614.3 1759.17
#Mann=3,-1,0
  4316.5    0.05       0  5095.5    0.03       0  5101.6    0.05       0
Bank Sta=5095.5,5101.6
Exp/Cntr=0.3,0.1

Type RM Length L Ch R = 1,28421,127,127,127
BEGIN DESCRIPTION:
Mapping XS 45f59ca4
END DESCRIPTION:
XS GIS Cut Line= 2
      1630110.83      6882087.29      1629947.77      6883454.20
#Sta/Elev= 30
  4194.2 1749.89  4200.6 1749.46  4288.1 1748.38  4365.6 1745.68  4458.1 1744.37
  4547.4 1742.41  4710.7 1741.72  4718.6 1741.58  4725.0 1740.56  4725.5 1740.06
  4731.9 1740.06  4732.4 1740.56  4738.7 1741.45  4758.9 1741.83  4793.2 1741.48
  4880.7 1741.78  5020.7 1740.69  5101.3 1742.25  5133.2 1743.50  5171.8 1745.75
  5191.9 1747.94  5202.0 1748.19  5262.4 1753.55  5298.2 1755.98  5312.8 1756.13
  5322.9 1756.97  5380.7 1758.86  5433.6 1761.27  5514.2 1763.50  5570.8 1764.31
#Mann=3,-1,0
  4194.2    0.05       0  4725.0    0.03       0  4732.4    0.05       0
Bank Sta=4725,4732.4
Exp/Cntr=0.3,0.1

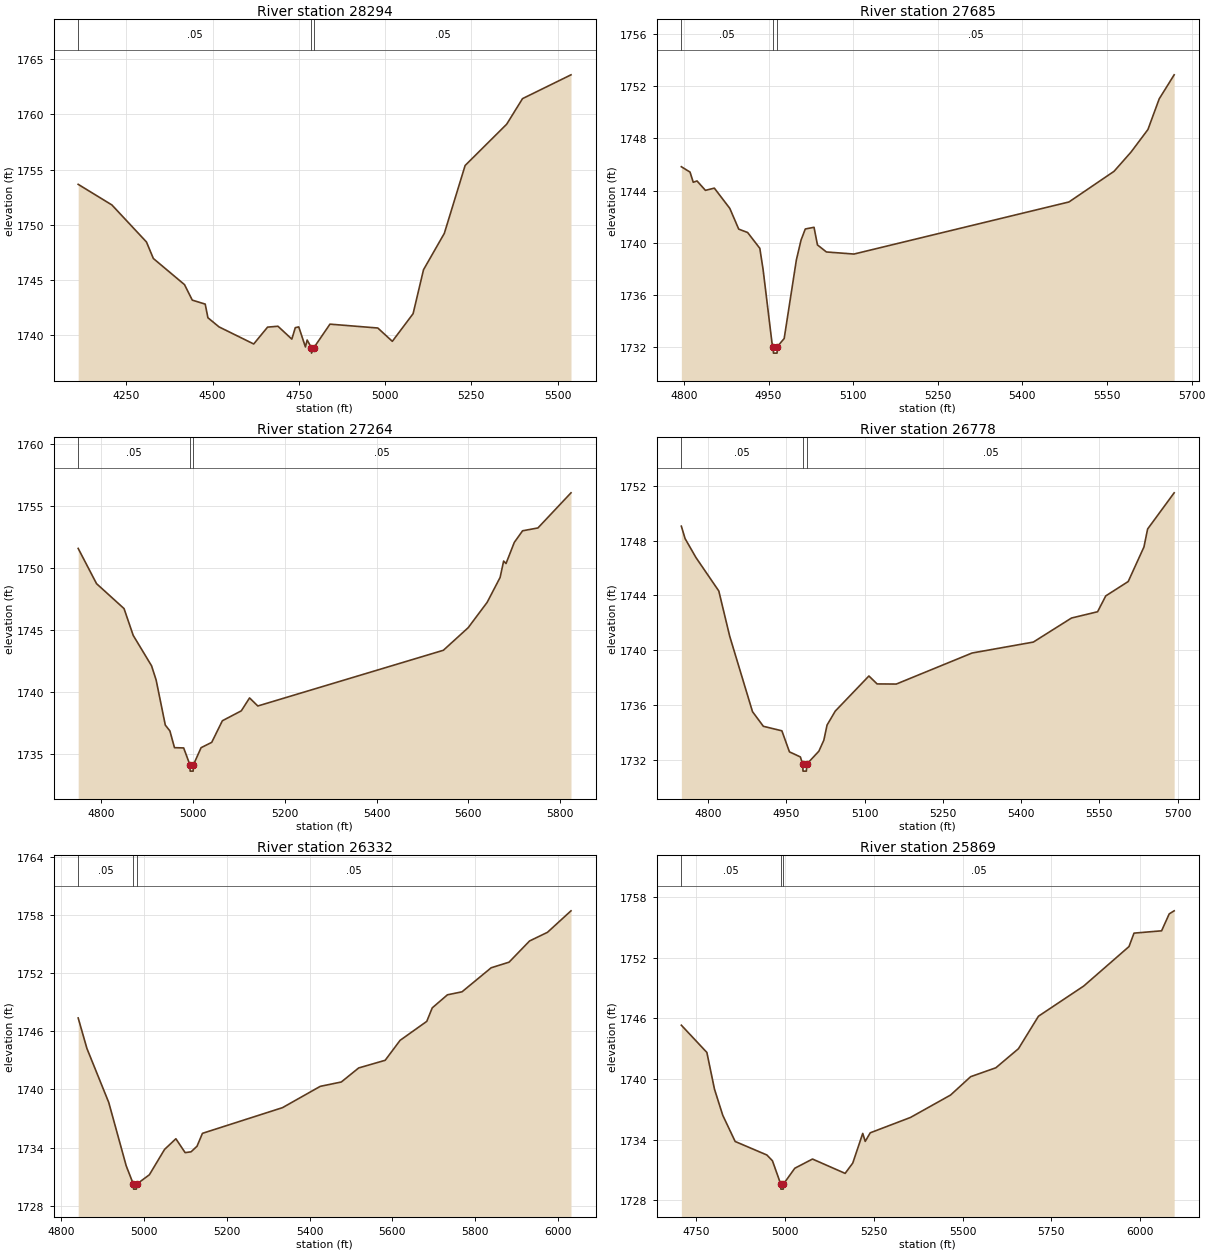
Type RM Length L Ch R = 1,28294,609,609,609
BEGIN DESCRIPTION:
Mapping XS 32de6a79
END DESCRIPTION:
XS GIS Cut Line= 3
      1629958.06      6882000.40      1629937.22      6882378.92
      1629836.58      6883423.49
#Sta/Elev= 30
  4110.4 1753.66  4208.1 1751.79  4308.3 1748.43  4328.3 1746.93  4418.5 1744.56
  4441.2 1743.15  4478.6 1742.79  4486.5 1741.55  4518.7 1740.72  4619.2 1739.17
  4659.4 1740.70  4689.5 1740.78  4729.7 1739.61  4739.7 1740.65  4749.8 1740.72
  4769.1 1738.90  4774.1 1739.53  4786.3 1738.84  4786.8 1738.34  4793.7 1738.84
  4840.2 1740.97  4978.9 1740.62  5021.0 1739.41  5081.2 1741.92  5111.4 1745.91
  5171.7 1749.21  5232.0 1755.37  5352.5 1759.12  5398.4 1761.44  5538.9 1763.60
#Mann=3,-1,0
  4110.4    0.05       0  4786.3    0.03       0  4793.7    0.05       0
Bank Sta=4786.3,4793.7
Exp/Cntr=0.3,0.1

Type RM Length L Ch R = 1,27685,421,421,421
BEGIN DESCRIPTION:
Mapping XS ecccecdb
END DESCRIPTION:
XS GIS Cut Line= 3
      1629880.03      6882233.87      1629605.71      6882713.05
      1629605.71      6883034.50
#Sta/Elev= 30
  4795.4 1745.83  4810.8 1745.42  4816.5 1744.64  4823.2 1744.74  4838.1 1744.02
  4853.9 1744.19  4881.3 1742.64  4897.1 1741.05  4912.9 1740.79  4934.5 1739.58
  4940.3 1737.96  4956.1 1732.33  4958.2 1732.05  4958.7 1731.55  4965.1 1731.55
  4965.6 1732.05  4977.7 1732.67  4999.3 1738.69  5007.6 1740.21  5015.1 1741.06
  5030.6 1741.19  5036.7 1739.84  5052.5 1739.30  5101.4 1739.14  5482.5 1743.13
  5562.5 1745.48  5592.5 1746.95  5622.5 1748.68  5642.5 1751.03  5669.0 1752.87
#Mann=3,-1,0
  4795.4    0.05       0  4958.2    0.05       0  4965.6    0.05       0
Bank Sta=4958.2,4965.6
Exp/Cntr=0.3,0.1

Type RM Length L Ch R = 1,27264,486,486,486
BEGIN DESCRIPTION:
Deadman 53 39.0
END DESCRIPTION:
XS GIS Cut Line= 3
      1629405.00      6882088.00      1629405.00      6882338.00
      1629605.00      6883137.98
#Sta/Elev= 30
  4749.3 1751.58  4789.3 1748.74  4849.3 1746.73  4869.3 1744.57  4909.3 1742.12
  4919.3 1740.97  4939.3 1737.34  4949.3 1736.87  4959.3 1735.52  4979.3 1735.50
  4993.0 1734.13  4993.5 1733.63  5000.0 1733.63  5000.5 1734.13  5017.3 1735.52
  5040.5 1735.95  5063.7 1737.69  5105.0 1738.49  5123.0 1739.53  5141.0 1738.88
  5545.6 1743.37  5599.7 1745.19  5641.0 1747.23  5669.3 1749.24  5677.0 1750.56
  5682.2 1750.36  5700.2 1752.06  5718.3 1753.00  5751.8 1753.23  5823.9 1756.06
#Mann=3,-1,0
  4749.3    0.05       0  4993.0    0.05       0  5000.5    0.05       0
Bank Sta=4993,5000.5
Exp/Cntr=0.3,0.1

Type RM Length L Ch R = 1,26778,446,446,446
BEGIN DESCRIPTION:
Deadman 53 38.0
END DESCRIPTION:
XS GIS Cut Line= 3
      1628805.03      6882238.04      1628955.00      6882438.00
      1629305.01      6883038.02
#Sta/Elev= 30
  4748.9 1749.07  4756.1 1748.16  4777.0 1746.77  4820.7 1744.33  4841.6 1741.02
  4885.3 1735.50  4906.1 1734.43  4941.6 1734.10  4956.1 1732.56  4977.0 1732.19
  4981.6 1731.65  4982.1 1731.15  4988.6 1731.15  4989.1 1731.65  5012.5 1732.61
  5022.0 1733.41  5028.2 1734.52  5043.9 1735.54  5108.4 1738.11  5124.1 1737.53
  5160.9 1737.52  5306.1 1739.79  5423.5 1740.59  5496.7 1742.35  5546.7 1742.81
  5562.4 1743.97  5605.4 1745.02  5635.6 1747.55  5642.6 1748.86  5693.5 1751.51
#Mann=3,-1,0
  4748.9    0.05       0  4981.6    0.05       0  4989.1    0.05       0
Bank Sta=4981.6,4989.1
Exp/Cntr=0.3,0.1

Type RM Length L Ch R = 1,26332,463,463,463
BEGIN DESCRIPTION:
Deadman 53 37.0
END DESCRIPTION:
XS GIS Cut Line= 3
      1628505.00      6882438.01      1628555.00      6882588.00
      1629205.01      6883388.02
#Sta/Elev= 30
  4841.9 1747.38  4863.0 1744.23  4915.7 1738.65  4957.8 1732.11  4975.1 1730.21
  4975.6 1729.71  4982.2 1729.71  4982.7 1730.21  5013.6 1731.19  5050.3 1733.81
  5077.6 1734.91  5099.9 1733.48  5114.2 1733.56  5128.6 1734.14  5141.7 1735.47
  5334.8 1738.12  5425.9 1740.32  5476.7 1740.77  5518.6 1742.22  5582.5 1743.01
  5618.5 1745.07  5682.9 1747.03  5696.0 1748.42  5732.7 1749.77  5767.9 1750.08
  5838.2 1752.56  5881.4 1753.14  5930.9 1755.33  5974.0 1756.22  6030.8 1758.44
#Mann=3,-1,0
  4841.9    0.05       0  4975.1    0.05       0  4982.7    0.05       0
Bank Sta=4975.1,4982.7
Exp/Cntr=0.3,0.1

Type RM Length L Ch R = 1,25869,514,514,514
BEGIN DESCRIPTION:
Deadman 53 36.0
END DESCRIPTION:
XS GIS Cut Line= 3
      1628005.00      6882538.01      1628155.00      6882788.00
      1628904.98      6883587.98
#Sta/Elev= 30
  4707.7 1745.33  4779.6 1742.63  4801.0 1739.00  4824.3 1736.41  4859.3 1733.81
  4948.7 1732.47  4964.3 1731.90  4987.6 1729.59  4988.1 1729.09  4994.8 1729.09
  4995.3 1729.59  5027.3 1731.16  5077.1 1732.07  5169.0 1730.65  5190.5 1731.67
  5218.6 1734.61  5225.6 1733.82  5239.8 1734.67  5353.1 1736.19  5466.0 1738.41
  5522.6 1740.23  5593.5 1741.11  5657.2 1743.00  5713.6 1746.22  5841.1 1749.21
  5968.6 1753.12  5982.7 1754.45  6060.4 1754.68  6081.9 1756.36  6095.8 1756.66
#Mann=3,-1,0
  4707.7    0.05       0  4987.6    0.03       0  4995.3    0.05       0
Bank Sta=4987.6,4995.3
Exp/Cntr=0.3,0.1

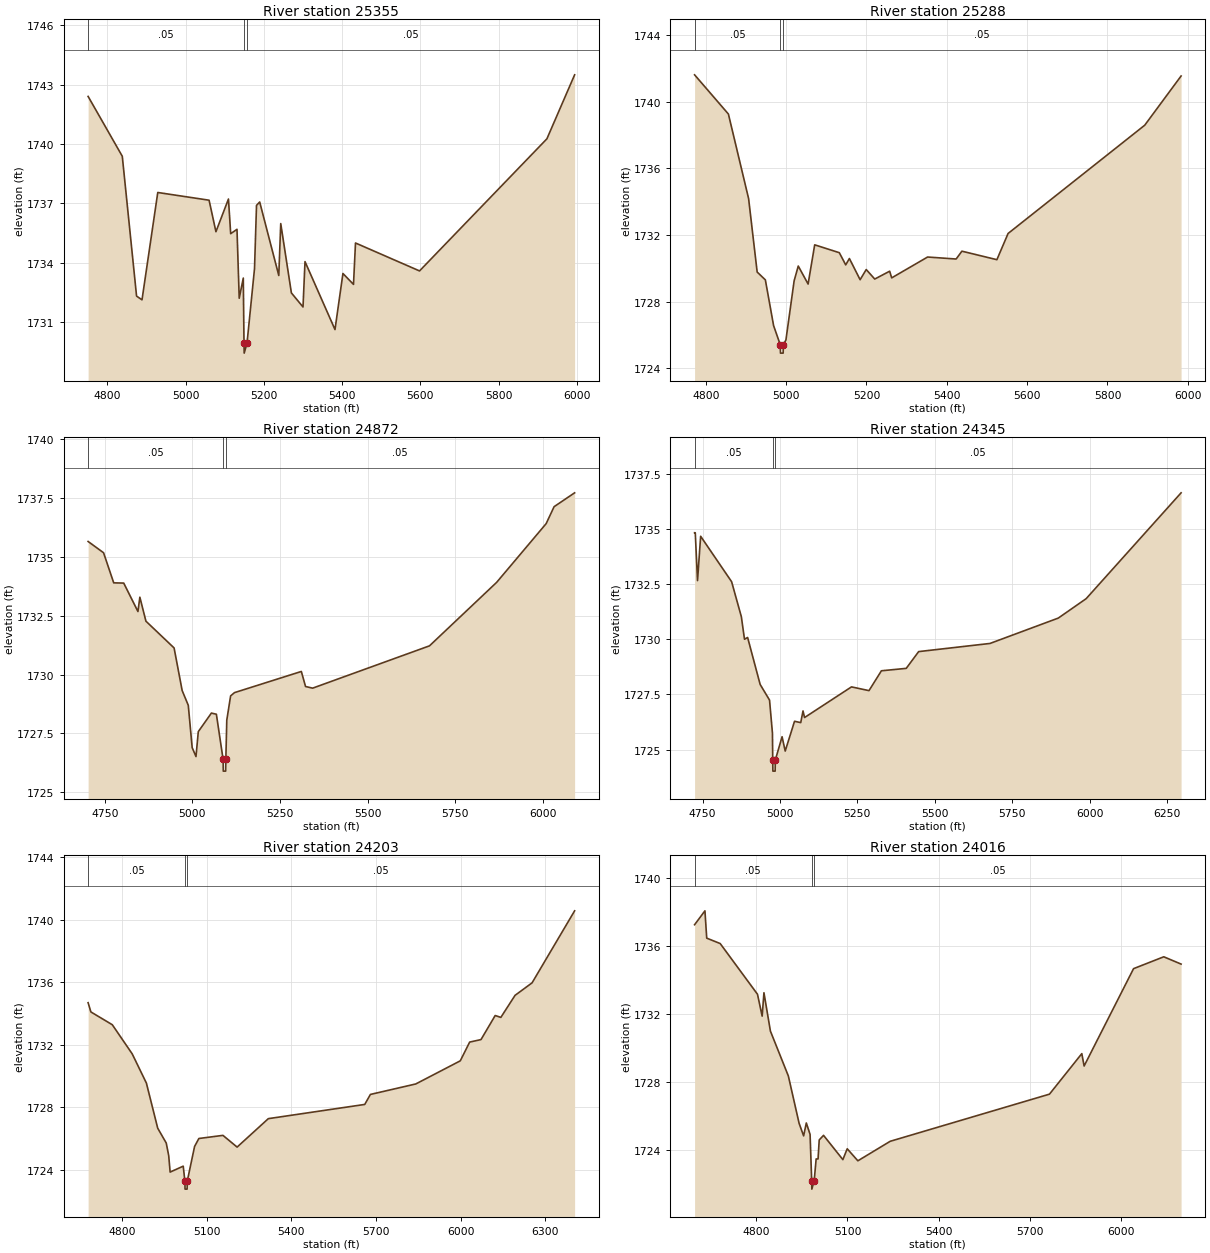
Type RM Length L Ch R = 1,25355,67,67,67
BEGIN DESCRIPTION:
Mapping XS c342686e
END DESCRIPTION:
XS GIS Cut Line= 5
      1627694.17      6882691.42      1627735.84      6883017.80
      1627805.28      6883056.00      1628173.34      6882996.97
      1628485.87      6883337.28
#Sta/Elev= 30
  4750.9 1742.40  4838.2 1739.38  4874.7 1732.32  4888.6 1732.13  4928.9 1737.55
  5060.0 1737.16  5077.5 1735.57  5109.5 1737.22  5115.2 1735.47  5131.3 1735.69
  5137.0 1732.21  5147.4 1733.23  5149.2 1729.94  5149.7 1729.44  5156.9 1729.94
  5176.1 1733.71  5181.2 1736.90  5189.3 1737.07  5238.1 1733.36  5243.1 1735.98
  5270.3 1732.48  5300.0 1731.77  5305.1 1734.06  5381.7 1730.63  5402.0 1733.46
  5429.0 1732.91  5434.1 1735.00  5597.7 1733.59  5923.2 1740.26  5994.0 1743.49
#Mann=3,-1,0
  4750.9    0.05       0  5149.2    0.03       0  5156.9    0.05       0
Bank Sta=5149.2,5156.9
Exp/Cntr=0.3,0.1

Type RM Length L Ch R = 1,25288,416,416,416
BEGIN DESCRIPTION:
Mapping XS b7cb82f1
END DESCRIPTION:
XS GIS Cut Line= 5
      1627610.83      6882715.70      1627690.70      6883087.25
      1627767.09      6883135.86      1628110.84      6883076.83
      1628377.26      6883364.02
#Sta/Elev= 30
  4772.1 1741.60  4856.3 1739.25  4906.6 1734.18  4927.9 1729.78  4948.3 1729.31
  4968.8 1726.57  4985.4 1725.42  4985.9 1724.92  4992.6 1724.92  4993.1 1725.42
  4999.5 1725.71  5019.9 1729.25  5030.2 1730.14  5054.7 1729.06  5071.1 1731.41
  5132.4 1730.94  5148.3 1730.21  5157.5 1730.59  5184.2 1729.32  5199.4 1729.93
  5220.6 1729.36  5257.7 1729.83  5262.8 1729.43  5352.2 1730.68  5423.2 1730.56
  5437.6 1731.03  5524.7 1730.52  5552.5 1732.09  5892.7 1738.58  5983.2 1741.53
#Mann=3,-1,0
  4772.1    0.05       0  4985.4    0.05       0  4993.1    0.05       0
Bank Sta=4985.4,4993.1
Exp/Cntr=0.3,0.1

Type RM Length L Ch R = 1,24872,527,527,527
BEGIN DESCRIPTION:
Mapping XS f03b79f3
END DESCRIPTION:
XS GIS Cut Line= 3
      1627149.05      6882767.85      1627364.31      6883240.03
      1628225.44      6883361.56
#Sta/Elev= 30
  4702.3 1735.66  4746.4 1735.18  4775.4 1733.90  4803.9 1733.89  4844.5 1732.68
  4850.0 1733.29  4867.3 1732.27  4947.7 1731.13  4970.7 1729.32  4988.2 1728.69
  4999.3 1726.89  5010.2 1726.51  5016.8 1727.57  5054.2 1728.36  5068.4 1728.31
  5087.6 1726.39  5088.1 1725.89  5094.9 1725.89  5095.4 1726.39  5098.1 1728.06
  5109.0 1729.09  5120.1 1729.23  5310.9 1730.13  5322.9 1729.49  5343.1 1729.42
  5676.7 1731.22  5868.3 1733.92  6009.7 1736.42  6032.3 1737.14  6090.9 1737.73
#Mann=3,-1,0
  4702.3    0.05       0  5087.6    0.05       0  5095.4    0.05       0
Bank Sta=5087.6,5095.4
Exp/Cntr=0.3,0.1

Type RM Length L Ch R = 1,24345,142,142,142
BEGIN DESCRIPTION:
Mapping XS 1267cc87
END DESCRIPTION:
XS GIS Cut Line= 3
      1626565.65      6883264.33      1626860.84      6883309.47
      1628130.79      6883392.75
#Sta/Elev= 30
  4724.4 1734.83  4726.6 1734.83  4733.9 1732.66  4744.0 1734.67  4844.0 1732.61
  4875.5 1731.02  4885.6 1730.00  4895.7 1730.08  4936.2 1727.95  4966.5 1727.24
  4975.9 1725.74  4976.8 1724.52  4977.3 1724.02  4984.6 1724.02  4985.1 1724.52
  5007.0 1725.58  5017.1 1724.93  5047.2 1726.28  5067.3 1726.22  5074.6 1726.75
  5079.6 1726.45  5231.2 1727.84  5287.7 1727.67  5327.8 1728.57  5408.0 1728.68
  5448.1 1729.44  5678.6 1729.81  5899.1 1730.96  5989.1 1731.84  6295.7 1736.64
#Mann=3,-1,0
  4724.4    0.05       0  4976.8    0.05       0  4985.1    0.05       0
Bank Sta=4976.8,4985.1
Exp/Cntr=0.3,0.1

Type RM Length L Ch R = 1,24203,187,187,187
BEGIN DESCRIPTION:
Mapping XS 4a28a08a
END DESCRIPTION:
XS GIS Cut Line= 3
      1626419.86      6883371.97      1626638.61      6883396.28
      1628135.12      6883542.11
#Sta/Elev= 30
  4680.3 1734.70  4690.1 1734.11  4766.0 1733.29  4836.4 1731.43  4886.7 1729.56
  4926.9 1726.67  4957.1 1725.72  4965.9 1724.91  4970.9 1723.86  5017.3 1724.24
  5023.2 1723.27  5023.7 1722.77  5031.0 1722.77  5031.5 1723.27  5057.5 1725.50
  5072.7 1726.01  5158.0 1726.21  5208.2 1725.46  5318.8 1727.28  5660.4 1728.19
  5680.5 1728.83  5841.2 1729.50  5998.9 1730.98  6032.1 1732.18  6072.3 1732.34
  6122.6 1733.88  6142.6 1733.76  6192.9 1735.17  6253.2 1735.97  6404.0 1740.58
#Mann=3,-1,0
  4680.3    0.05       0  5023.2    0.03       0  5031.5    0.05       0
Bank Sta=5023.2,5031.5
Exp/Cntr=0.3,0.1

Type RM Length L Ch R = 1,24016,471,471,471
BEGIN DESCRIPTION:
Deadman 53 32.0
END DESCRIPTION:
XS GIS Cut Line= 3
      1626263.58      6883323.34      1626605.00      6883538.00
      1627513.61      6884319.88
#Sta/Elev= 30
  4596.6 1737.26  4630.7 1738.08  4636.6 1736.47  4681.0 1736.15  4803.8 1733.16
  4819.1 1731.87  4825.0 1733.25  4846.3 1730.99  4905.4 1728.34  4940.8 1725.55
  4955.7 1724.81  4964.5 1725.57  4976.9 1724.90  4982.2 1722.17  4982.7 1721.67
  4990.5 1722.17  4996.9 1723.45  5003.2 1723.45  5007.0 1724.57  5021.3 1724.84
  5084.9 1723.41  5099.2 1724.05  5134.3 1723.34  5240.7 1724.49  5765.2 1727.27
  5871.7 1729.66  5879.3 1728.93  6042.1 1734.67  6141.6 1735.37  6198.6 1734.94
#Mann=3,-1,0
  4596.6    0.05       0  4982.2    0.05       0  4990.5    0.05       0
Bank Sta=4982.2,4990.5
Exp/Cntr=0.3,0.1