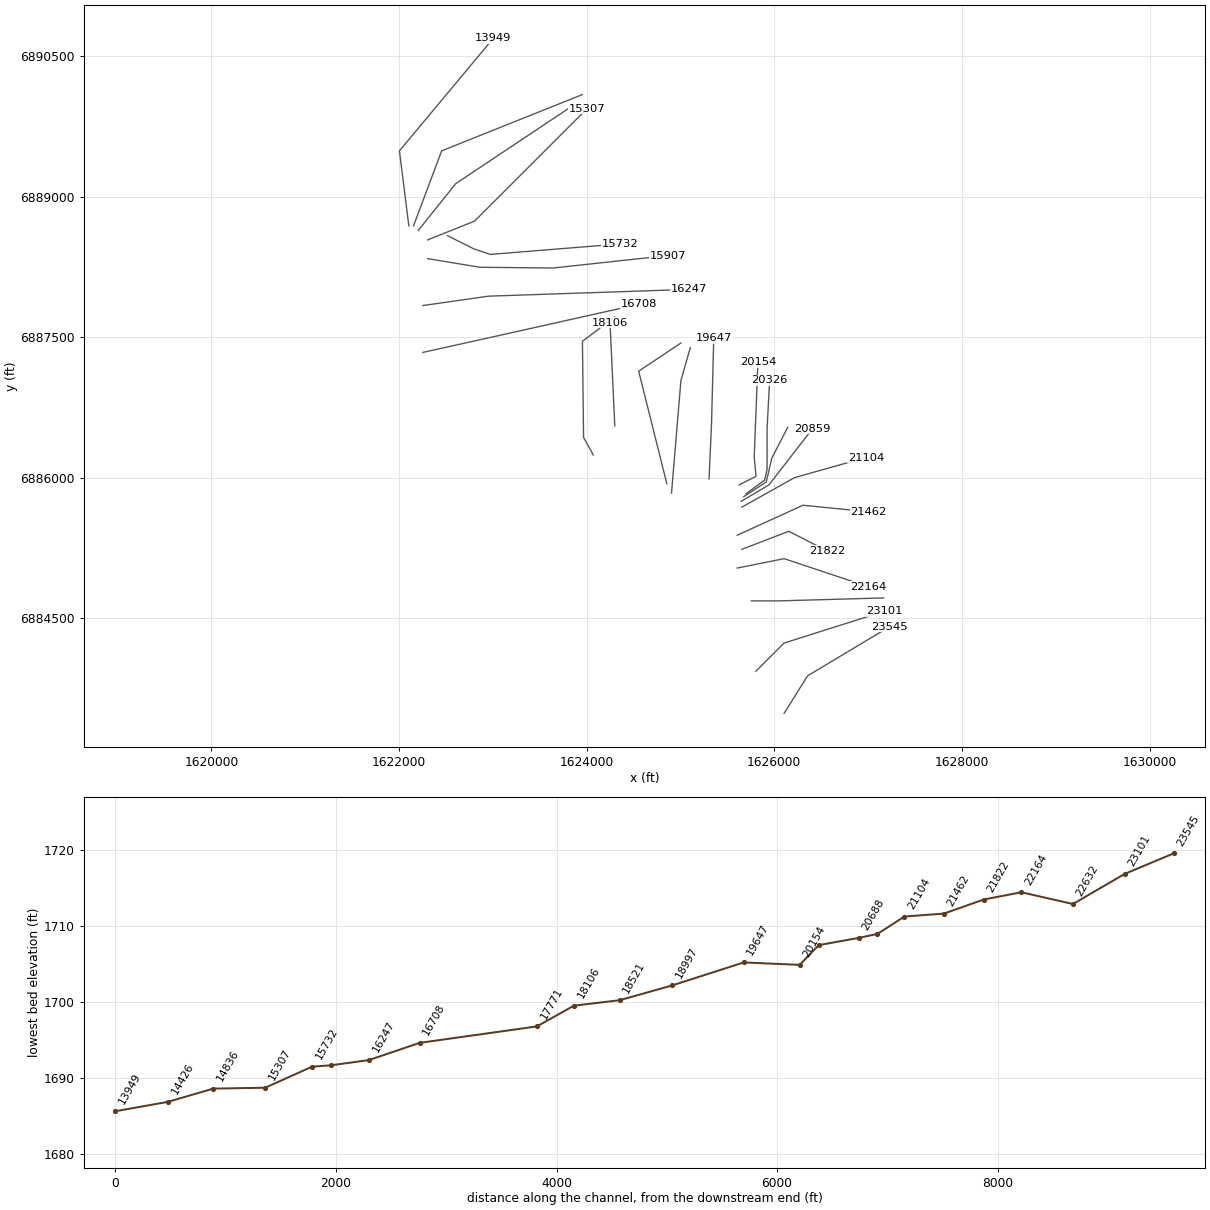
HEC-RAS study Deadman 53.prj: Deadman 53 Base Level Engineering

--- Deadman 53.g01 (geometry) --- (continued)

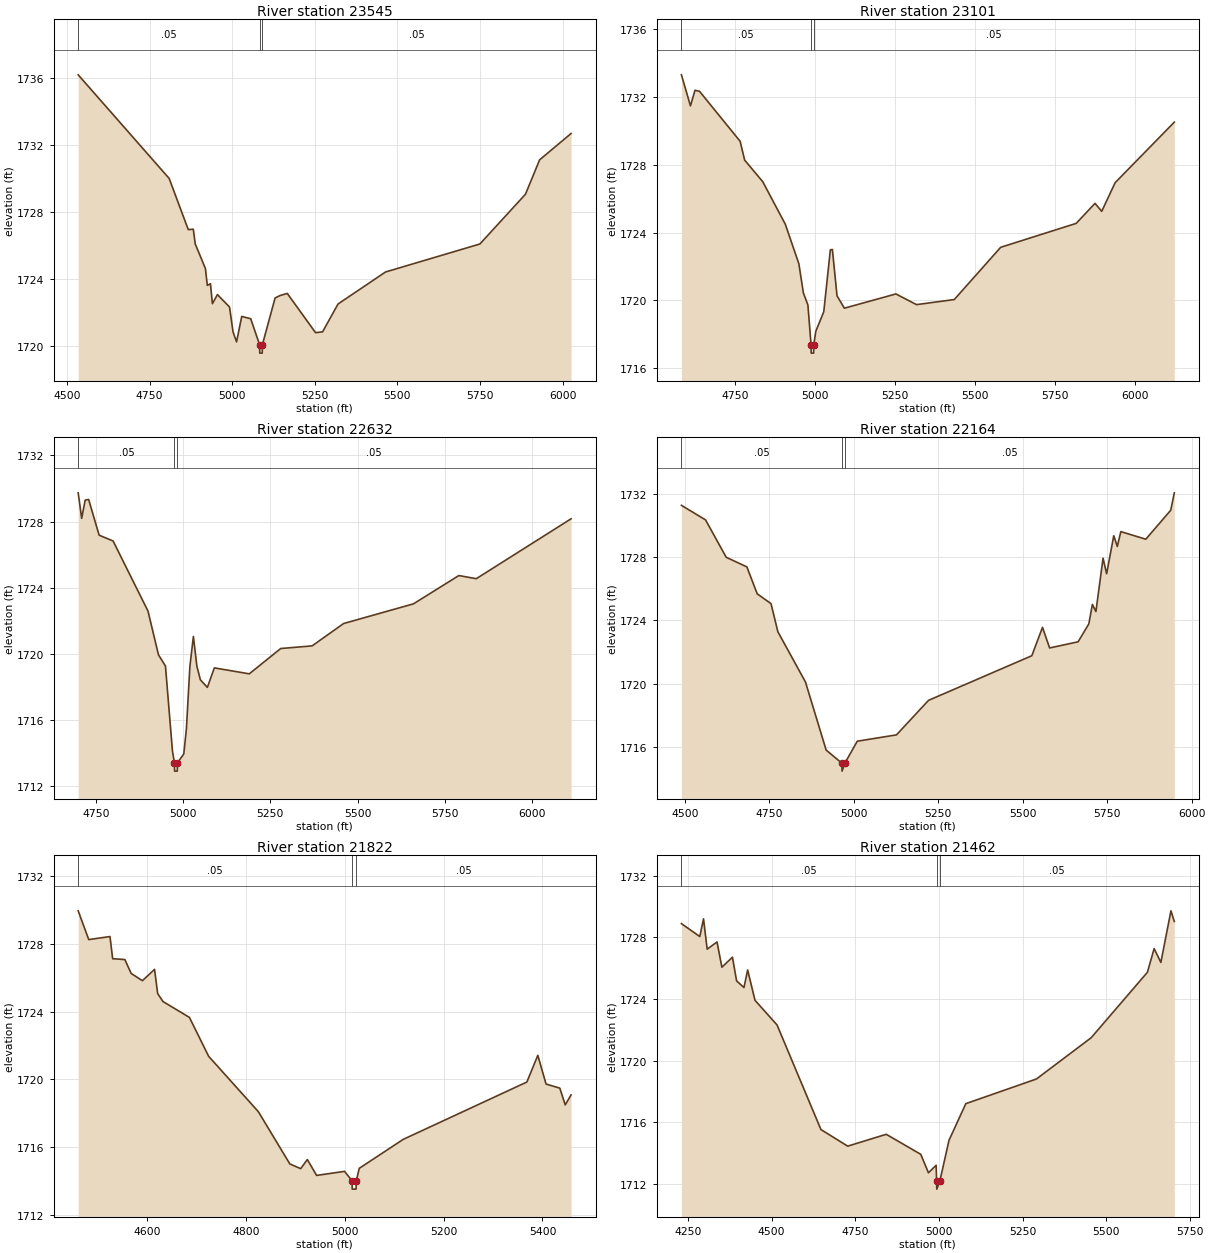
Type RM Length L Ch R = 1,23545,444,444,444
BEGIN DESCRIPTION:
Deadman 53 31.0
END DESCRIPTION:
XS GIS Cut Line= 3
      1626104.99      6883487.98      1626355.00      6883888.00
      1627229.96      6884412.98
#Sta/Elev= 30
  4533.8 1736.19  4809.2 1730.01  4867.0 1726.96  4882.3 1726.98  4888.2 1726.10
  4918.9 1724.64  4924.7 1723.63  4934.2 1723.73  4940.1 1722.54  4955.4 1723.08
  4992.0 1722.34  5002.6 1720.85  5013.3 1720.26  5028.9 1721.78  5056.1 1721.64
  5083.0 1720.09  5083.5 1719.59  5090.9 1719.59  5091.4 1720.09  5129.9 1722.88
  5145.5 1723.03  5166.8 1723.15  5252.4 1720.81  5273.7 1720.86  5320.4 1722.52
  5464.2 1724.43  5749.9 1726.10  5887.9 1729.07  5930.7 1731.12  6025.9 1732.69
#Mann=3,-1,0
  4533.8    0.05       0  5083.0    0.05       0  5091.4    0.05       0
Bank Sta=5083,5091.4
Exp/Cntr=0.3,0.1

Type RM Length L Ch R = 1,23101,469,469,469
BEGIN DESCRIPTION:
Deadman 53 30.0
END DESCRIPTION:
XS GIS Cut Line= 3
      1625804.98      6883937.98      1626105.00      6884238.00
      1627171.65      6884576.30
#Sta/Elev= 30
  4581.2 1733.30  4609.5 1731.47  4623.7 1732.39  4637.8 1732.33  4765.1 1729.38
  4779.2 1728.27  4835.8 1727.00  4906.5 1724.49  4948.9 1722.16  4963.1 1720.44
  4977.2 1719.73  4987.1 1717.39  4987.6 1716.89  4995.1 1716.89  4995.6 1717.39
  5002.0 1718.18  5026.9 1719.33  5047.5 1722.98  5053.9 1723.00  5068.4 1720.27
  5091.4 1719.54  5252.8 1720.38  5317.3 1719.75  5435.6 1720.05  5580.8 1723.13
  5817.2 1724.54  5876.2 1725.72  5897.2 1725.25  5939.2 1726.94  6124.5 1730.51
#Mann=3,-1,0
  4581.2    0.05       0  4987.1    0.05       0  4995.6    0.05       0
Bank Sta=4987.1,4995.6
Exp/Cntr=0.3,0.1

Type RM Length L Ch R = 1,22632,468,468,468
BEGIN DESCRIPTION:
Deadman 53 29.0
END DESCRIPTION:
XS GIS Cut Line= 3
      1625755.01      6884688.00      1626055.00      6884688.00
      1627166.37      6884719.19
#Sta/Elev= 30
  4699.6 1729.74  4709.6 1728.20  4719.6 1729.30  4729.6 1729.34  4759.6 1727.18
  4799.6 1726.83  4899.6 1722.59  4929.6 1719.95  4949.6 1719.27  4969.6 1714.14
  4975.3 1713.42  4975.8 1712.92  4983.4 1712.92  4983.9 1713.42  5002.1 1713.96
  5009.6 1715.48  5019.6 1719.26  5029.6 1721.06  5039.6 1719.26  5049.6 1718.44
  5069.6 1717.98  5089.6 1719.16  5189.7 1718.80  5279.7 1720.33  5369.7 1720.49
  5459.8 1721.84  5659.9 1723.03  5789.9 1724.74  5839.9 1724.55  6111.4 1728.17
#Mann=3,-1,0
  4699.6    0.05       0  4975.3    0.05       0  4983.9    0.05       0
Bank Sta=4975.3,4983.9
Exp/Cntr=0.3,0.1

Type RM Length L Ch R = 1,22164,342,342,342
BEGIN DESCRIPTION:
Deadman 53 28.0
END DESCRIPTION:
XS GIS Cut Line= 3
      1625605.03      6885038.01      1626105.00      6885138.00
      1627005.05      6884837.98
#Sta/Elev= 30
  4490.1 1731.26  4561.5 1730.34  4622.6 1727.98  4683.8 1727.37  4714.4 1725.67
  4755.2 1725.05  4775.6 1723.27  4857.2 1720.10  4918.4 1715.80  4965.0 1714.97
  4965.5 1714.47  4973.7 1714.97  5010.5 1716.36  5126.5 1716.76  5221.3 1718.94
  5527.0 1721.76  5558.6 1723.55  5579.7 1722.25  5664.0 1722.64  5695.7 1723.77
  5706.2 1725.00  5716.7 1724.55  5737.8 1727.92  5748.4 1726.94  5769.5 1729.34
  5780.0 1728.66  5790.5 1729.60  5864.3 1729.12  5938.1 1730.95  5948.7 1732.05
#Mann=3,-1,0
  4490.1    0.05       0  4965.0    0.05       0  4973.7    0.05       0
Bank Sta=4965,4973.7
Exp/Cntr=0.3,0.1

Type RM Length L Ch R = 1,21822,360,360,360
BEGIN DESCRIPTION:
Deadman 53 27.0
END DESCRIPTION:
XS GIS Cut Line= 3
      1625655.00      6885238.00      1626155.32      6885429.92
      1626565.42      6885220.15
#Sta/Elev= 30
  4461.3 1729.96  4482.7 1728.26  4525.6 1728.44  4531.0 1727.13  4555.7 1727.08
  4568.4 1726.26  4591.1 1725.83  4615.7 1726.50  4622.0 1725.07  4632.7 1724.60
  4686.2 1723.66  4725.1 1721.36  4825.5 1718.09  4889.2 1715.00  4911.1 1714.72
  4924.6 1715.26  4943.3 1714.32  4999.8 1714.56  5014.9 1714.01  5015.4 1713.51
  5023.1 1713.51  5023.6 1714.01  5029.6 1714.74  5118.4 1716.45  5368.4 1719.84
  5390.6 1721.42  5407.2 1719.72  5435.0 1719.48  5446.0 1718.49  5457.8 1719.08
#Mann=3,-1,0
  4461.3    0.05       0  5014.9    0.05       0  5023.6    0.05       0
Bank Sta=5014.9,5023.6
Exp/Cntr=0.3,0.1

Type RM Length L Ch R = 1,21462,358,358,358
BEGIN DESCRIPTION:
Deadman 53 26.0
END DESCRIPTION:
XS GIS Cut Line= 3
      1625604.99      6885387.99      1626306.15      6885708.02
      1627005.01      6885638.00
#Sta/Elev= 30
  4230.4 1728.90  4285.3 1728.06  4296.4 1729.21  4307.4 1727.24  4336.8 1727.71
  4351.3 1726.07  4382.9 1726.72  4395.3 1725.18  4417.3 1724.75  4428.3 1725.89
  4450.3 1723.92  4516.2 1722.32  4647.3 1715.53  4727.4 1714.45  4842.5 1715.22
  4945.7 1713.92  4968.7 1712.72  4991.7 1713.21  4993.1 1712.16  4993.6 1711.66
  5002.5 1712.16  5030.1 1714.83  5080.4 1717.21  5291.4 1718.81  5455.0 1721.49
  5623.1 1725.74  5643.2 1727.28  5663.3 1726.38  5693.4 1729.73  5703.5 1729.04
#Mann=3,-1,0
  4230.4    0.05       0  4993.1    0.05       0  5002.5    0.05       0
Bank Sta=4993.1,5002.5
Exp/Cntr=0.3,0.1

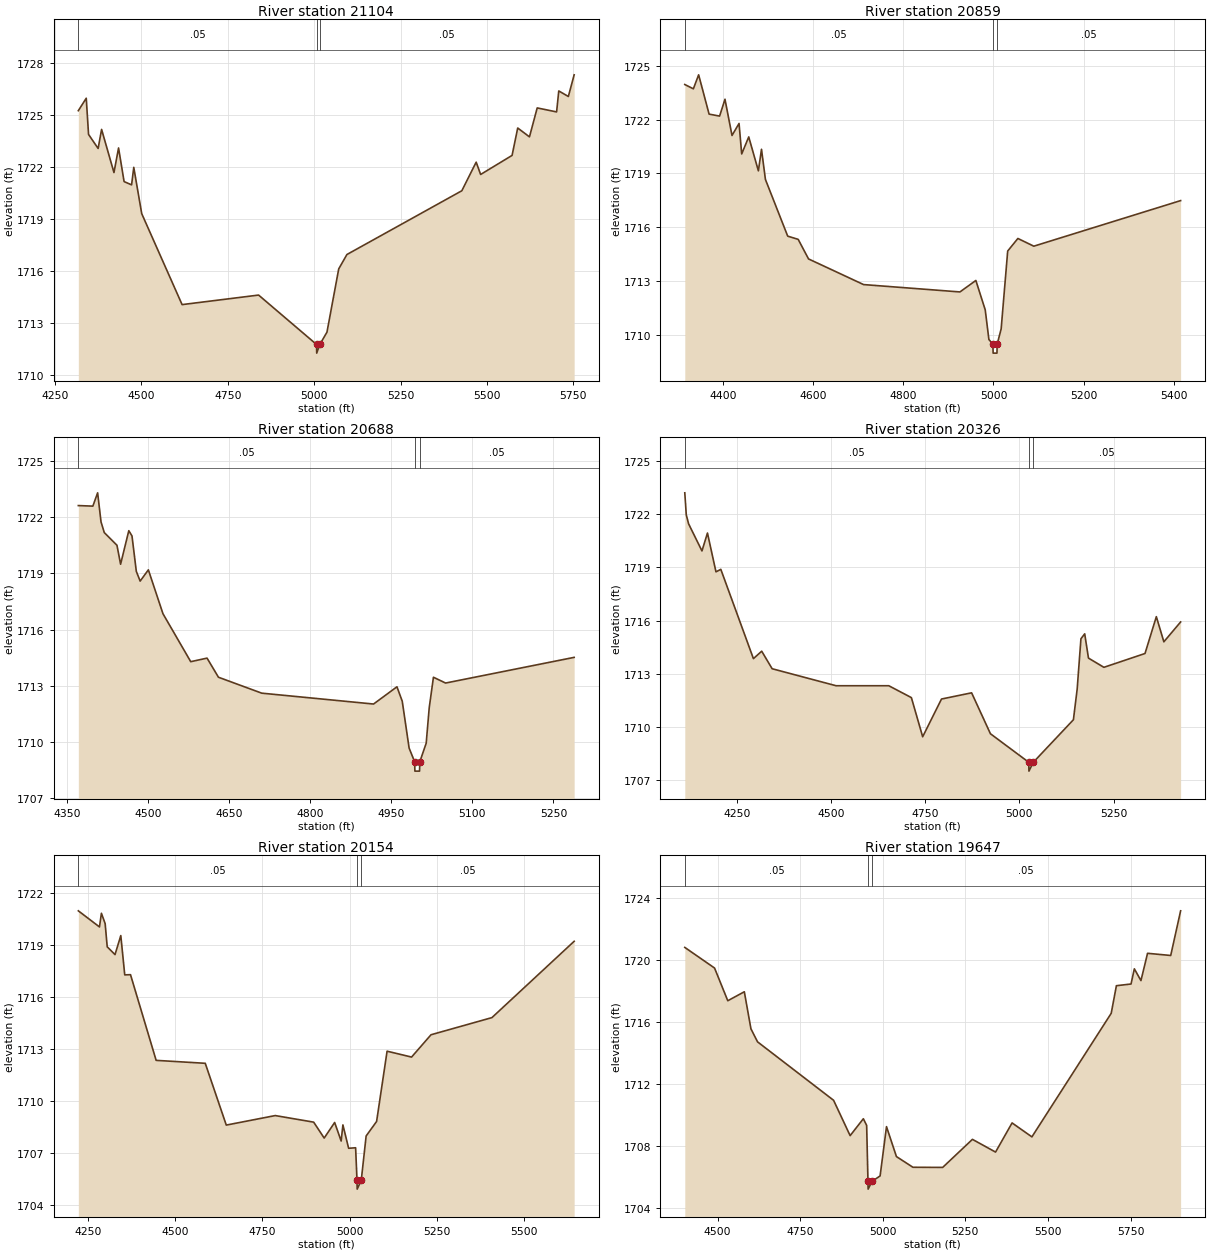
Type RM Length L Ch R = 1,21104,245,245,245
BEGIN DESCRIPTION:
Deadman 53 25.0
END DESCRIPTION:
XS GIS Cut Line= 3
      1625655.02      6885688.01      1626216.59      6886002.61
      1626977.87      6886217.09
#Sta/Elev= 30
  4317.6 1725.26  4340.5 1725.98  4347.2 1723.89  4374.9 1723.08  4384.9 1724.18
  4420.7 1721.69  4434.0 1723.11  4450.0 1721.17  4471.7 1720.98  4478.0 1721.99
  4501.0 1719.32  4617.8 1714.07  4839.2 1714.62  5006.8 1711.77  5007.3 1711.27
  5016.3 1711.77  5037.0 1712.48  5071.0 1716.13  5094.7 1716.96  5427.2 1720.64
  5468.7 1722.29  5481.6 1721.58  5572.6 1722.68  5588.9 1724.26  5622.9 1723.75
  5645.3 1725.42  5701.4 1725.19  5707.7 1726.40  5735.4 1726.08  5752.2 1727.33
#Mann=3,-1,0
  4317.6    0.05       0  5006.8    0.05       0  5016.3    0.05       0
Bank Sta=5006.8,5016.3
Exp/Cntr=0.3,0.1

Type RM Length L Ch R = 1,20859,171,171,171
BEGIN DESCRIPTION:
Mapping XS 595e1cfb
END DESCRIPTION:
XS GIS Cut Line= 3
      1625648.59      6885750.42      1625943.21      6885924.84
      1626407.29      6886523.19
#Sta/Elev= 30
  4315.4 1723.95  4334.4 1723.71  4346.1 1724.49  4369.3 1722.30  4392.6 1722.19
  4404.5 1723.13  4420.1 1721.11  4435.7 1721.78  4441.6 1720.08  4457.2 1721.03
  4478.6 1719.14  4485.5 1720.34  4494.2 1718.66  4543.6 1715.50  4566.9 1715.32
  4589.8 1714.23  4711.9 1712.80  4925.6 1712.39  4960.9 1713.03  4981.7 1711.39
  4989.8 1709.74  4998.7 1709.48  4999.2 1708.98  5007.7 1708.98  5008.2 1709.48
  5017.0 1710.33  5031.5 1714.67  5054.1 1715.37  5089.4 1714.94  5415.0 1717.48
#Mann=3,-1,0
  4315.4    0.05       0  4998.7    0.05       0  5008.2    0.05       0
Bank Sta=4998.7,5008.2
Exp/Cntr=0.3,0.1

Type RM Length L Ch R = 1,20688,362,362,362
BEGIN DESCRIPTION:
Mapping XS 65bc107a
END DESCRIPTION:
XS GIS Cut Line= 4
      1625675.13      6885799.83      1625914.74      6885956.11
      1625973.77      6886209.58      1626143.92      6886539.46
#Sta/Elev= 30
  4370.9 1722.62  4397.8 1722.59  4406.6 1723.30  4412.9 1721.75  4418.9 1721.18
  4442.4 1720.50  4449.1 1719.49  4464.3 1721.28  4470.2 1721.00  4478.2 1719.11
  4485.3 1718.59  4500.5 1719.19  4527.5 1716.85  4578.9 1714.29  4609.1 1714.48
  4630.2 1713.46  4710.3 1712.61  4917.2 1712.03  4960.5 1712.95  4970.3 1712.18
  4983.0 1709.68  4993.2 1708.95  4993.7 1708.45  5002.3 1708.45  5002.8 1708.95
  5014.6 1709.94  5020.2 1711.83  5028.0 1713.46  5050.5 1713.15  5288.4 1714.52
#Mann=3,-1,0
  4370.9    0.05       0  4993.2    0.05       0  5002.8    0.05       0
Bank Sta=4993.2,5002.8
Exp/Cntr=0.3,0.1

Type RM Length L Ch R = 1,20326,172,172,172
BEGIN DESCRIPTION:
Mapping XS e2950e08
END DESCRIPTION:
XS GIS Cut Line= 5
      1625698.48      6885829.48      1625897.89      6885977.05
      1625923.64      6886090.01      1625923.64      6886529.61
      1625951.12      6887042.44
#Sta/Elev= 30
  4111.2 1723.21  4115.1 1721.97  4121.3 1721.46  4156.8 1719.93  4171.4 1720.94
  4194.0 1718.75  4206.9 1718.89  4293.5 1713.85  4315.5 1714.27  4343.2 1713.28
  4513.1 1712.32  4653.1 1712.32  4713.1 1711.65  4743.1 1709.44  4793.1 1711.57
  4873.1 1711.92  4923.1 1709.61  5024.9 1708.00  5025.4 1707.50  5037.0 1708.00
  5143.5 1710.40  5153.5 1712.13  5163.5 1714.97  5173.5 1715.25  5183.5 1713.88
  5224.5 1713.36  5333.7 1714.14  5363.8 1716.22  5383.8 1714.80  5428.3 1715.92
#Mann=3,-1,0
  4111.2    0.05       0  5024.9    0.03       0  5037.0    0.05       0
Bank Sta=5024.9,5037
Exp/Cntr=0.3,0.1

Type RM Length L Ch R = 1,20154,507,507,507
BEGIN DESCRIPTION:
Mapping XS 380dac1c
END DESCRIPTION:
XS GIS Cut Line= 4
      1625626.64      6885925.18      1625806.15      6886016.93
      1625786.27      6886221.28      1625826.09      6887233.18
#Sta/Elev= 30
  4223.0 1720.98  4283.5 1720.05  4289.1 1720.84  4299.8 1720.24  4305.7 1718.90
  4328.0 1718.45  4344.6 1719.55  4355.9 1717.28  4372.4 1717.29  4445.8 1712.34
  4586.4 1712.17  4646.6 1708.60  4786.8 1709.15  4896.8 1708.77  4926.9 1707.85
  4956.9 1708.75  4975.5 1707.68  4980.5 1708.61  4996.9 1707.26  5016.9 1707.29
  5020.9 1705.40  5021.4 1704.90  5033.0 1705.40  5047.0 1707.97  5077.0 1708.81
  5107.0 1712.87  5177.1 1712.53  5232.8 1713.82  5407.2 1714.81  5642.6 1719.22
#Mann=3,-1,0
  4223.0    0.05       0  5020.9    0.05       0  5033.0    0.05       0
Bank Sta=5020.9,5033
Exp/Cntr=0.3,0.1

Type RM Length L Ch R = 1,19647,650,650,650
BEGIN DESCRIPTION:
Deadman 53 22.0
END DESCRIPTION:
XS GIS Cut Line= 3
      1625305.00      6885988.02      1625331.41      6886574.16
      1625355.00      6887488.02
#Sta/Elev= 30
  4400.8 1720.81  4490.9 1719.48  4530.9 1717.37  4581.0 1717.95  4601.0 1715.56
  4621.0 1714.72  4851.2 1710.95  4901.3 1708.67  4941.3 1709.76  4951.3 1709.33
  4955.3 1705.72  4955.8 1705.22  4967.4 1705.72  4992.0 1706.07  5011.4 1709.25
  5041.4 1707.32  5091.4 1706.63  5181.4 1706.62  5271.5 1708.43  5341.5 1707.61
  5391.5 1709.49  5451.5 1708.59  5691.6 1716.56  5707.3 1718.34  5751.6 1718.45
  5761.6 1719.43  5781.6 1718.67  5801.6 1720.43  5871.7 1720.29  5901.7 1723.17
#Mann=3,-1,0
  4400.8    0.05       0  4955.3    0.05       0  4967.4    0.05       0
Bank Sta=4955.3,4967.4
Exp/Cntr=0.3,0.1

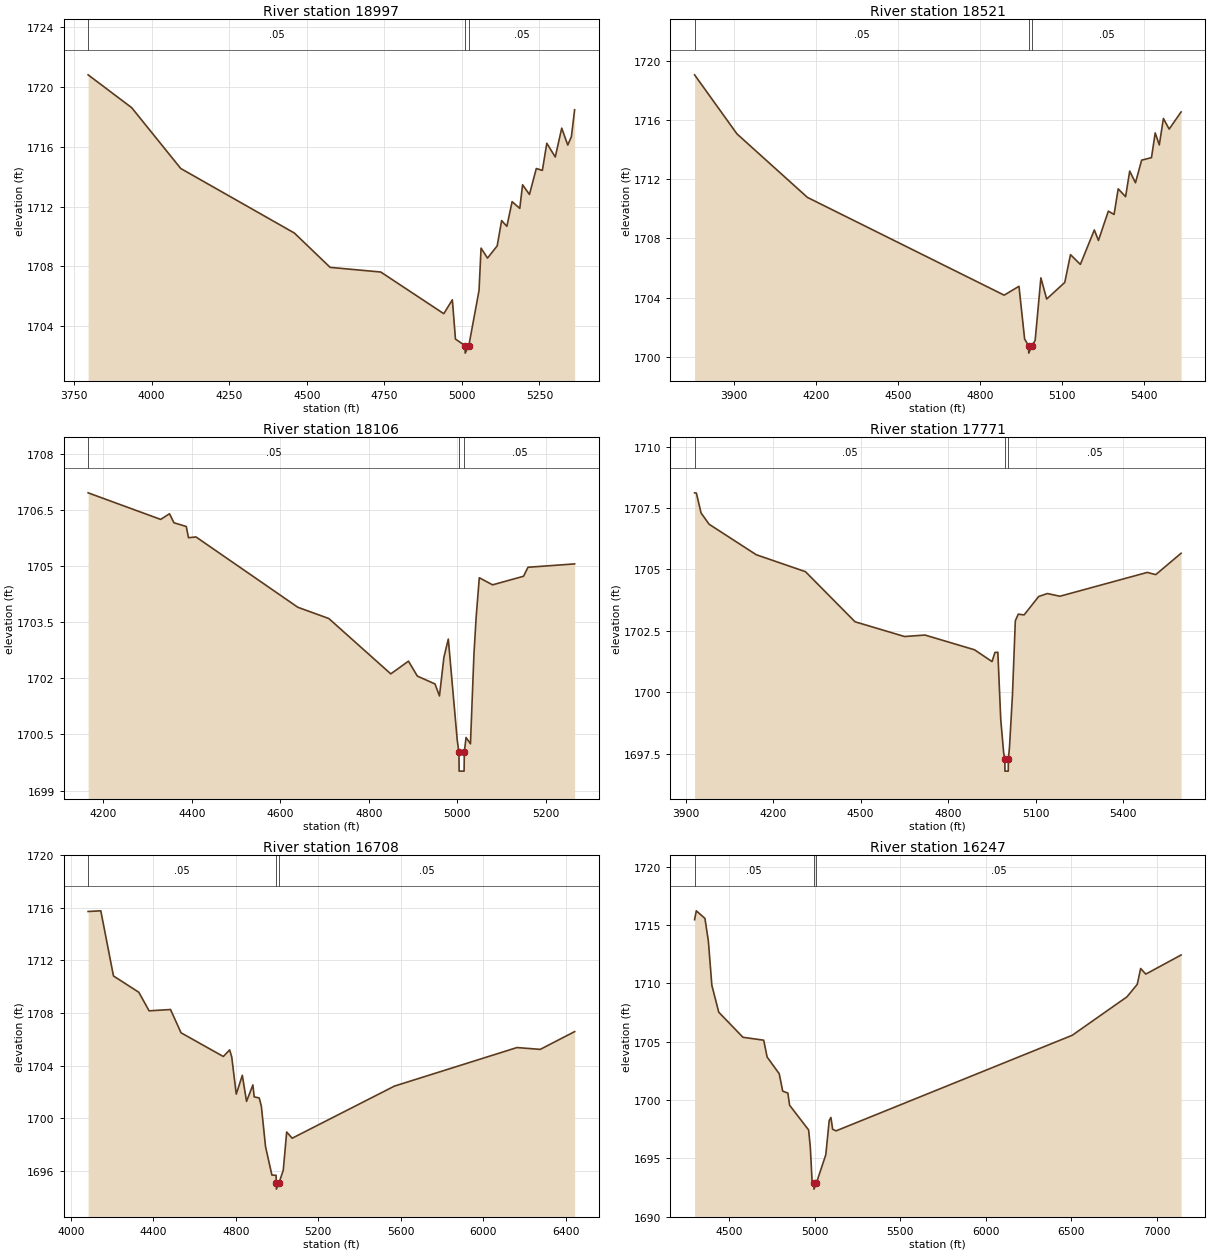
Type RM Length L Ch R = 1,18997,476,476,476
BEGIN DESCRIPTION:
Deadman 53 21.0
END DESCRIPTION:
XS GIS Cut Line= 3
      1624905.00      6885837.96      1625005.00      6887038.00
      1625105.00      6887388.00
#Sta/Elev= 30
  3795.4 1720.82  3935.9 1718.62  4094.0 1714.55  4460.2 1710.23  4575.6 1707.93
  4738.7 1707.62  4941.9 1704.83  4969.5 1705.76  4979.5 1703.13  5010.4 1702.69
  5010.9 1702.19  5022.6 1702.69  5055.5 1706.39  5062.0 1709.22  5082.8 1708.55
  5114.0 1709.37  5128.3 1711.06  5145.2 1710.68  5162.1 1712.33  5186.8 1711.88
  5195.9 1713.46  5218.0 1712.81  5240.1 1714.55  5259.6 1714.42  5273.9 1716.24
  5301.2 1715.32  5322.0 1717.25  5341.5 1716.12  5353.2 1716.68  5363.6 1718.48
#Mann=3,-1,0
  3795.4    0.05       0  5010.4    0.05       0  5022.6    0.05       0
Bank Sta=5010.4,5022.6
Exp/Cntr=0.3,0.1

Type RM Length L Ch R = 1,18521,415,415,415
BEGIN DESCRIPTION:
Deadman 53 20.0
END DESCRIPTION:
XS GIS Cut Line= 3
      1624855.01      6885937.96      1624555.00      6887138.00
      1625004.99      6887438.00
#Sta/Elev= 30
  3756.8 1719.06  3911.5 1715.07  4169.2 1710.77  4888.1 1704.16  4942.2 1704.76
  4962.9 1701.19  4977.4 1700.74  4977.9 1700.24  4989.6 1700.74  5001.3 1701.10
  5022.3 1705.33  5043.4 1703.90  5109.5 1705.02  5130.5 1706.90  5166.5 1706.24
  5217.6 1708.57  5232.6 1707.86  5268.7 1709.84  5289.7 1709.62  5304.8 1711.35
  5331.8 1710.82  5346.8 1712.55  5367.9 1711.76  5390.4 1713.29  5426.4 1713.46
  5440.0 1715.13  5455.0 1714.32  5470.0 1716.11  5491.0 1715.39  5534.6 1716.55
#Mann=3,-1,0
  3756.8    0.05       0  4977.4    0.05       0  4989.6    0.05       0
Bank Sta=4977.4,4989.6
Exp/Cntr=0.3,0.1

Type RM Length L Ch R = 1,18106,335,335,335
BEGIN DESCRIPTION:
Mapping XS 21d16651
END DESCRIPTION:
XS GIS Cut Line= 2
      1624300.37      6886554.14      1624249.63      6887653.37
#Sta/Elev= 30
  4165.3 1706.96  4329.3 1706.25  4349.4 1706.40  4359.4 1706.16  4387.3 1706.06
  4392.3 1705.76  4409.4 1705.78  4639.7 1703.90  4709.7 1703.60  4849.9 1702.12
  4889.9 1702.46  4910.0 1702.06  4950.0 1701.85  4960.0 1701.53  4970.0 1702.56
  4980.0 1703.05  5000.1 1700.36  5004.0 1700.02  5004.5 1699.52  5015.7 1699.52
  5016.2 1700.02  5020.1 1700.42  5030.1 1700.25  5038.0 1702.65  5043.0 1703.64
  5050.1 1704.69  5080.1 1704.50  5150.2 1704.73  5160.2 1704.97  5265.7 1705.06
#Mann=3,-1,0
  4165.3    0.05       0  5004.0    0.05       0  5016.2    0.05       0
Bank Sta=5004,5016.2
Exp/Cntr=0.3,0.1

Type RM Length L Ch R = 1,17771,1063,1063,1063
BEGIN DESCRIPTION:
Mapping XS 80c639ea
END DESCRIPTION:
XS GIS Cut Line= 4
      1624071.21      6886244.28      1623967.52      6886431.72
      1623955.55      6887456.73      1624298.52      6887715.95
#Sta/Elev= 30
  3930.2 1708.12  3936.4 1708.11  3952.5 1707.30  3980.2 1706.84  4141.8 1705.60
  4310.7 1704.91  4480.7 1702.87  4650.7 1702.27  4720.7 1702.33  4890.7 1701.73
  4950.7 1701.25  4960.7 1701.62  4970.7 1701.63  4980.7 1698.88  4990.7 1697.53
  4994.6 1697.29  4995.1 1696.79  5006.4 1696.79  5006.9 1697.29  5010.7 1697.77
  5020.7 1699.86  5030.7 1702.91  5040.7 1703.18  5060.8 1703.15  5110.8 1703.90
  5140.8 1704.02  5183.7 1703.91  5483.4 1704.88  5512.5 1704.79  5599.4 1705.66
#Mann=3,-1,0
  3930.2    0.05       0  4994.6   0.035       0  5006.9    0.05       0
Bank Sta=4994.6,5006.9
Exp/Cntr=0.3,0.1

Type RM Length L Ch R = 1,16708,461,461,461
BEGIN DESCRIPTION:
Deadman 53 19.0
END DESCRIPTION:
XS GIS Cut Line= 3
      1622254.95      6887337.99      1623155.00      6887538.00
      1624557.78      6887851.57
#Sta/Elev= 30
  4083.6 1715.72  4145.1 1715.77  4206.6 1710.82  4329.5 1709.58  4379.4 1708.17
  4483.2 1708.27  4534.4 1706.50  4739.3 1704.70  4770.0 1705.20  4780.2 1704.66
  4802.0 1701.84  4831.5 1703.27  4851.9 1701.29  4882.7 1702.54  4889.1 1701.63
  4913.4 1701.55  4923.7 1700.93  4944.1 1697.84  4974.9 1695.69  4995.4 1695.67
  4996.1 1695.12  4996.6 1694.62  5009.9 1695.12  5029.9 1696.05  5046.6 1698.96
  5073.3 1698.49  5569.2 1702.45  6163.5 1705.38  6276.2 1705.24  6443.0 1706.59
#Mann=3,-1,0
  4083.6    0.05       0  4996.1   0.035       0  5009.9    0.05       0
Bank Sta=4996.1,5009.9
Exp/Cntr=0.3,0.1

Type RM Length L Ch R = 1,16247,340,340,340
BEGIN DESCRIPTION:
Deadman 53 18.0
END DESCRIPTION:
XS GIS Cut Line= 3
      1622254.97      6887838.00      1622955.00      6887938.00
      1625091.25      6888010.18
#Sta/Elev= 30
  4298.4 1715.47  4308.5 1716.23  4359.0 1715.58  4379.2 1713.61  4399.4 1709.84
  4439.8 1707.53  4581.3 1705.38  4702.5 1705.13  4722.7 1703.68  4793.4 1702.25
  4813.6 1700.76  4843.9 1700.59  4854.0 1699.55  4965.1 1697.43  4975.2 1695.95
  4985.3 1693.03  4996.1 1692.85  4996.6 1692.35  5010.0 1692.85  5065.6 1695.30
  5085.6 1698.24  5095.6 1698.50  5105.6 1697.49  5125.6 1697.35  6506.4 1705.55
  6826.6 1708.85  6886.6 1709.92  6906.6 1711.28  6936.6 1710.80  7143.0 1712.44
#Mann=3,-1,0
  4298.4    0.05       0  4996.1    0.05       0  5010.0    0.05       0
Bank Sta=4996.1,5010
Exp/Cntr=0.3,0.1

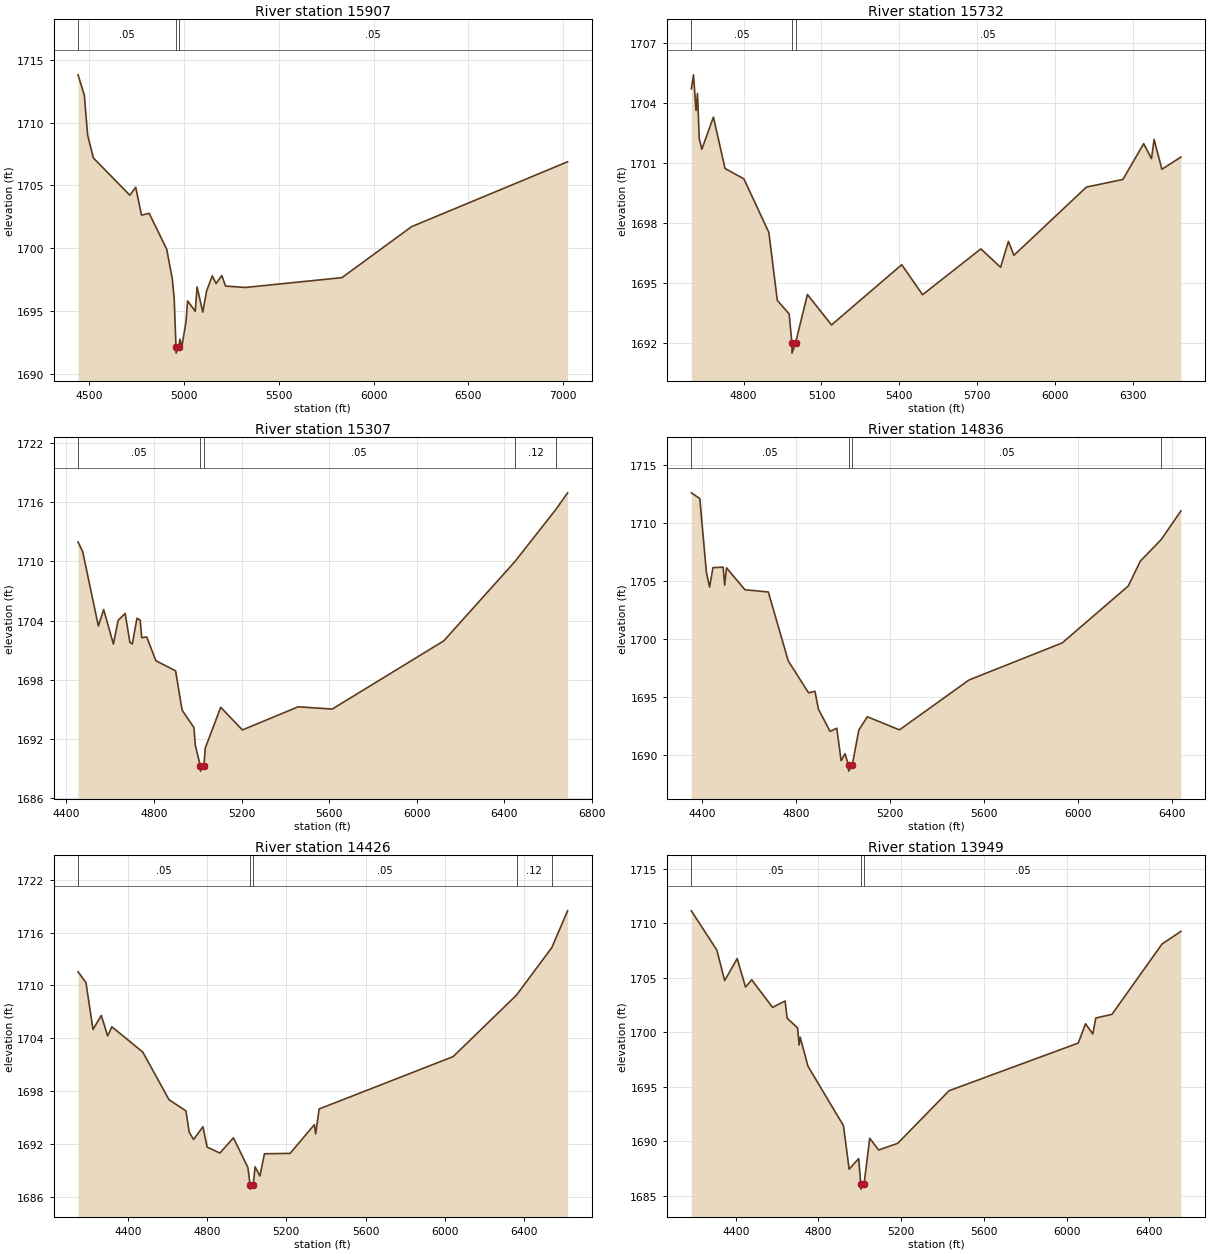
Type RM Length L Ch R = 1,15907,175,175,175
BEGIN DESCRIPTION:
Deadman 53 17.0
END DESCRIPTION:
XS GIS Cut Line= 4
      1622305.00      6888338.00      1622863.33      6888246.33
      1623641.10      6888238.12      1624870.18      6888371.32
#Sta/Elev= 30
  4442.6 1713.79  4475.8 1712.18  4493.3 1708.99  4523.7 1707.18  4715.8 1704.22
  4746.6 1704.85  4777.0 1702.64  4817.6 1702.78  4909.7 1699.94  4939.2 1697.59
  4949.3 1696.04  4958.9 1692.17  4959.4 1691.67  4972.8 1692.17  4979.7 1692.78
  4989.8 1692.19  5011.7 1694.18  5020.1 1695.82  5060.1 1695.00  5070.1 1696.93
  5100.1 1694.93  5120.1 1696.61  5150.1 1697.81  5170.1 1697.20  5200.1 1697.84
  5220.1 1697.00  5324.5 1696.89  5833.5 1697.67  6200.1 1701.72  7022.5 1706.88
#Mann=3,-1,0
  4442.6    0.05       0  4958.9    0.05       0  4972.8    0.05       0
Bank Sta=4958.9,4972.8
Exp/Cntr=0.3,0.1

Type RM Length L Ch R = 1,15732,425,425,425
BEGIN DESCRIPTION:
Mapping XS 7c3e2ea0
END DESCRIPTION:
XS GIS Cut Line= 4
      1622517.60      6888582.97      1622797.11      6888443.22
      1622972.78      6888383.33      1624358.18      6888495.12
#Sta/Elev= 30
  4598.3 1704.69  4606.6 1705.39  4616.4 1703.61  4622.0 1704.46  4628.9 1702.20
  4638.7 1701.67  4683.5 1703.28  4728.2 1700.71  4800.9 1700.19  4897.3 1697.51
  4929.7 1694.12  4975.4 1693.44  4986.1 1691.98  4986.6 1691.48  5000.0 1691.98
  5045.9 1694.41  5138.8 1692.89  5409.6 1695.90  5489.9 1694.40  5714.8 1696.69
  5790.9 1695.77  5821.0 1697.07  5842.2 1696.37  6121.9 1699.78  6262.4 1700.16
  6342.7 1701.95  6372.8 1701.20  6382.8 1702.16  6412.9 1700.67  6486.3 1701.28
#Mann=3,-1,0
  4598.3    0.05       0  4986.1    0.03       0  5000.0    0.05       0
Bank Sta=4986.1,5000
Exp/Cntr=0.3,0.1

Type RM Length L Ch R = 1,15307,471,471,471
BEGIN DESCRIPTION:
Deadman 53 16.0
END DESCRIPTION:
XS GIS Cut Line= 3
      1622305.03      6888538.01      1622805.00      6888738.00
      1624004.97      6889937.97
#Sta/Elev= 30
  4452.9 1711.97  4474.4 1710.98  4545.8 1703.44  4570.0 1705.11  4614.4 1701.61
  4636.0 1704.02  4668.3 1704.71  4689.8 1701.78  4700.6 1701.61  4722.1 1704.23
  4736.9 1704.04  4743.7 1702.26  4766.6 1702.33  4808.3 1699.92  4898.5 1698.89
  4928.1 1694.90  4982.0 1693.14  4988.7 1691.30  5011.8 1689.21  5012.3 1688.71
  5027.5 1689.21  5033.8 1691.05  5104.5 1695.19  5203.5 1692.89  5458.1 1695.24
  5613.6 1695.01  6122.8 1701.93  6446.9 1709.96  6635.8 1715.30  6688.4 1716.96
#Mann=5,-1,0
  4452.9    0.05       0  5011.8    0.03       0  5027.5    0.05       0
  6446.9    0.12       0  6635.8    0.05       0
Bank Sta=5011.8,5027.5
Exp/Cntr=0.3,0.1

Type RM Length L Ch R = 1,14836,410,410,410
BEGIN DESCRIPTION:
Deadman 53 15.0
END DESCRIPTION:
XS GIS Cut Line= 3
      1622205.01      6888638.01      1622605.00      6889138.00
      1623804.98      6889937.99
#Sta/Elev= 30
  4354.8 1712.59  4390.8 1712.09  4418.8 1705.74  4432.4 1704.46  4446.8 1706.14
  4490.1 1706.18  4496.5 1704.63  4504.5 1706.12  4582.9 1704.23  4682.1 1704.04
  4767.0 1698.10  4853.4 1695.34  4880.6 1695.48  4895.1 1693.95  4944.7 1692.02
  4973.5 1692.29  4991.9 1689.49  5008.6 1690.09  5023.3 1689.09  5023.8 1688.59
  5039.0 1689.09  5067.2 1692.13  5103.3 1693.28  5240.0 1692.15  5535.9 1696.45
  5932.5 1699.65  6213.5 1704.56  6264.6 1706.70  6353.4 1708.56  6437.3 1711.03
#Mann=4,-1,0
  4354.8    0.05       0  5023.3    0.03       0  5039.0    0.05       0
  6353.4    0.12       0
Bank Sta=5023.3,5039
Exp/Cntr=0.3,0.1

Type RM Length L Ch R = 1,14426,477,477,477
BEGIN DESCRIPTION:
Deadman 53 14.0
END DESCRIPTION:
XS GIS Cut Line= 3
      1622155.01      6888688.04      1622455.00      6889488.00
      1623954.99      6890088.00
#Sta/Elev= 30
  4149.3 1711.56  4189.3 1710.33  4224.9 1705.00  4266.7 1706.59  4298.8 1704.26
  4320.1 1705.30  4475.9 1702.43  4608.5 1697.01  4693.9 1695.74  4710.0 1693.33
  4732.2 1692.49  4779.4 1693.94  4800.7 1691.63  4864.8 1690.95  4933.3 1692.68
  5006.4 1689.30  5017.3 1687.35  5017.8 1686.85  5033.0 1687.35  5042.7 1689.39
  5066.9 1688.33  5089.8 1690.87  5219.1 1690.91  5341.6 1694.18  5348.3 1693.12
  5365.8 1695.96  6041.6 1701.91  6361.7 1708.91  6539.4 1714.30  6619.2 1718.48
#Mann=5,-1,0
  4149.3    0.05       0  5017.3    0.05       0  5033.0    0.05       0
  6361.7    0.12       0  6539.4    0.05       0
Bank Sta=5017.3,5033
Exp/Cntr=0.3,0.1

Type RM Length L Ch R = 1,13949,425,425,425
BEGIN DESCRIPTION:
Deadman 53 13.0
END DESCRIPTION:
XS GIS Cut Line= 3
      1622105.00      6888688.03      1622005.00      6889488.00
      1623004.97      6890687.97
#Sta/Elev= 30
  4185.1 1711.14  4308.5 1707.54  4346.3 1704.74  4406.8 1706.76  4447.1 1704.15
  4477.3 1704.81  4578.1 1702.28  4638.6 1702.87  4648.6 1701.29  4699.0 1700.40
  4706.6 1698.83  4711.6 1699.55  4749.4 1696.88  4920.7 1691.44  4948.5 1687.44
  4994.5 1688.41  5004.7 1686.11  5005.2 1685.61  5020.9 1686.11  5047.9 1690.28
  5090.9 1689.20  5183.3 1689.81  5431.9 1694.64  6056.7 1699.01  6091.9 1700.78
  6127.0 1699.84  6141.4 1701.31  6219.5 1701.64  6461.6 1708.09  6553.3 1709.26
#Mann=3,-1,0
  4185.1    0.05       0  5004.7    0.05       0  5020.9    0.05       0
Bank Sta=5004.7,5020.9
Exp/Cntr=0.3,0.1