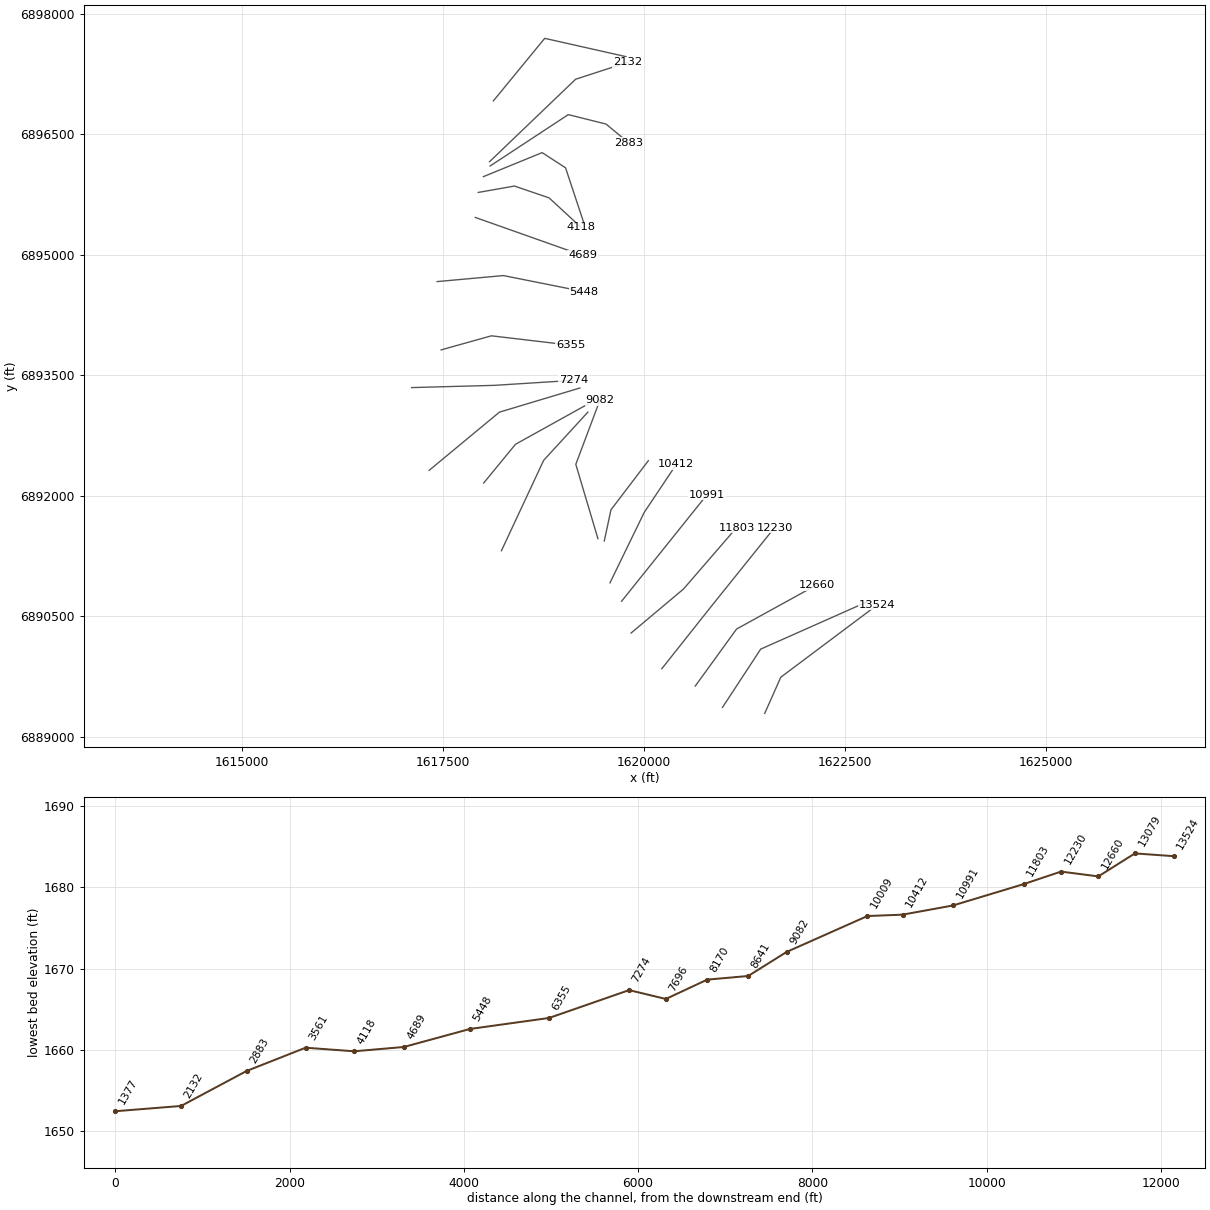
HEC-RAS study Deadman 53.prj: Deadman 53 Base Level Engineering

--- Deadman 53.g01 (geometry) --- (continued)

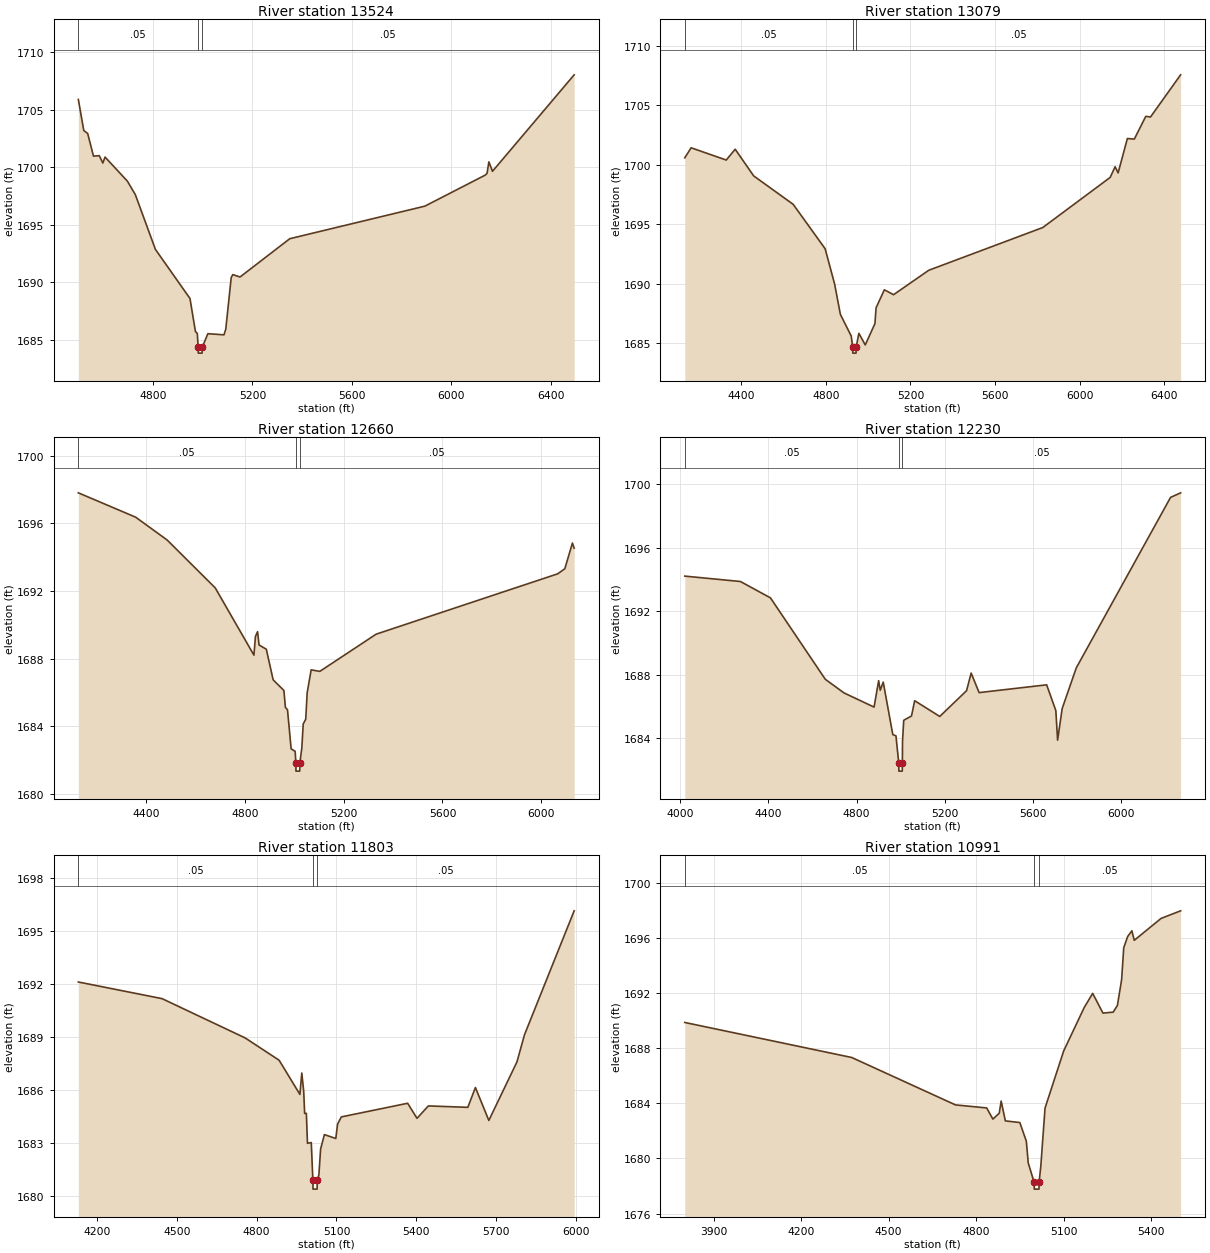
Type RM Length L Ch R = 1,13524,445,445,445
BEGIN DESCRIPTION:
Deadman 53 12.0
END DESCRIPTION:
XS GIS Cut Line= 3
      1621504.99      6889287.98      1621705.00      6889738.00
      1622905.03      6890638.02
#Sta/Elev= 30
  4500.5 1705.90  4522.4 1703.20  4538.1 1702.94  4561.4 1700.97  4584.6 1701.01
  4599.0 1700.37  4607.9 1700.89  4697.5 1698.80  4729.6 1697.62  4810.3 1692.86
  4949.2 1688.59  4971.1 1685.72  4978.6 1685.55  4982.1 1684.34  4982.6 1683.84
  4997.8 1683.84  4998.3 1684.34  5021.1 1685.53  5085.7 1685.43  5093.0 1685.92
  5114.8 1690.40  5121.1 1690.67  5150.3 1690.46  5350.3 1693.79  5893.0 1696.62
  6135.7 1699.32  6143.0 1699.48  6150.3 1700.47  6164.8 1699.65  6493.0 1708.04
#Mann=3,-1,0
  4500.5    0.05       0  4982.1    0.05       0  4998.3    0.05       0
Bank Sta=4982.1,4998.3
Exp/Cntr=0.3,0.1

Type RM Length L Ch R = 1,13079,419,419,419
BEGIN DESCRIPTION:
Deadman 53 11.0
END DESCRIPTION:
XS GIS Cut Line= 3
      1620979.99      6889362.99      1621455.00      6890088.00
      1622805.01      6890688.00
#Sta/Elev= 30
  4133.5 1700.59  4163.4 1701.43  4329.5 1700.40  4371.7 1701.31  4459.1 1699.07
  4646.0 1696.68  4797.0 1692.95  4842.0 1689.97  4869.1 1687.43  4920.4 1685.61
  4927.4 1684.68  4927.9 1684.18  4943.1 1684.18  4943.6 1684.68  4956.5 1685.84
  4986.7 1684.87  5032.4 1686.66  5037.9 1687.99  5076.9 1689.50  5120.6 1689.09
  5286.8 1691.14  5825.8 1694.73  6144.5 1698.94  6167.8 1699.84  6182.1 1699.32
  6225.9 1702.21  6258.7 1702.16  6312.8 1704.07  6335.3 1704.02  6477.6 1707.56
#Mann=3,-1,0
  4133.5    0.05       0  4927.4    0.05       0  4943.6    0.05       0
Bank Sta=4927.4,4943.6
Exp/Cntr=0.3,0.1

Type RM Length L Ch R = 1,12660,430,430,430
BEGIN DESCRIPTION:
Deadman 53 10.0
END DESCRIPTION:
XS GIS Cut Line= 3
      1620641.13      6889628.30      1621155.00      6890338.00
      1622148.10      6890885.25
#Sta/Elev= 30
  4123.7 1697.81  4356.1 1696.37  4483.7 1695.02  4678.6 1692.19  4835.6 1688.21
  4841.7 1689.31  4850.3 1689.60  4856.4 1688.81  4885.8 1688.56  4913.5 1686.75
  4957.0 1686.12  4963.2 1685.12  4971.7 1684.98  4986.4 1682.67  5002.8 1682.52
  5005.5 1681.85  5006.0 1681.35  5021.3 1681.35  5021.8 1681.85  5029.7 1682.71
  5035.4 1684.14  5045.6 1684.42  5051.5 1685.99  5067.6 1687.34  5102.7 1687.25
  5331.0 1689.45  6067.2 1693.02  6096.0 1693.32  6126.8 1694.84  6133.8 1694.54
#Mann=3,-1,0
  4123.7    0.05       0  5005.5    0.03       0  5021.8    0.05       0
Bank Sta=5005.5,5021.8
Exp/Cntr=0.3,0.1

Type RM Length L Ch R = 1,12230,427,427,427
BEGIN DESCRIPTION:
Mapping XS b243a369
END DESCRIPTION:
XS GIS Cut Line= 3
      1620224.46      6889843.57      1620835.56      6890614.39
      1621627.19      6891600.47
#Sta/Elev= 30
  4021.3 1694.21  4273.7 1693.87  4409.8 1692.84  4658.3 1687.72  4743.2 1686.86
  4879.5 1685.97  4900.3 1687.63  4907.5 1687.03  4921.1 1687.54  4964.4 1684.24
  4978.8 1684.16  4991.5 1682.44  4992.0 1681.94  5007.3 1681.94  5007.8 1682.44
  5008.5 1683.81  5014.0 1685.14  5049.2 1685.41  5063.6 1686.37  5177.3 1685.38
  5298.9 1687.00  5319.7 1688.11  5355.8 1686.88  5662.1 1687.37  5703.7 1685.75
  5711.7 1683.89  5732.5 1685.88  5796.5 1688.44  6223.8 1699.16  6269.5 1699.45
#Mann=3,-1,0
  4021.3    0.05       0  4991.5    0.03       0  5007.8    0.05       0
Bank Sta=4991.5,5007.8
Exp/Cntr=0.3,0.1

Type RM Length L Ch R = 1,11803,812,812,812
BEGIN DESCRIPTION:
Mapping XS 870e02f3
END DESCRIPTION:
XS GIS Cut Line= 3
      1619842.53      6890288.02      1620495.28      6890836.61
      1621155.00      6891600.50
#Sta/Elev= 30
  4130.5 1692.10  4444.9 1691.16  4757.1 1688.94  4884.6 1687.68  4962.6 1685.75
  4969.7 1686.96  4976.9 1685.92  4980.4 1684.68  4986.8 1684.68  4991.0 1682.99
  5005.3 1683.03  5011.3 1680.90  5011.8 1680.40  5027.2 1680.40  5027.7 1680.90
  5033.8 1681.20  5040.4 1682.67  5054.6 1683.48  5097.4 1683.26  5104.0 1684.07
  5118.3 1684.48  5367.2 1685.25  5402.3 1684.40  5445.1 1685.10  5593.2 1685.02
  5621.7 1686.14  5672.1 1684.28  5777.8 1687.59  5806.0 1689.12  5992.5 1696.12
#Mann=3,-1,0
  4130.5    0.05       0  5011.3   0.035       0  5027.7    0.05       0
Bank Sta=5011.3,5027.7
Exp/Cntr=0.3,0.1

Type RM Length L Ch R = 1,10991,579,579,579
BEGIN DESCRIPTION:
Mapping XS fcaeea5d
END DESCRIPTION:
XS GIS Cut Line= 2
      1619724.47      6890683.86      1620786.92      6892010.19
#Sta/Elev= 30
  3801.6 1689.86  4373.7 1687.32  4729.4 1683.88  4836.2 1683.66  4857.6 1682.85
  4879.4 1683.28  4885.9 1684.16  4900.3 1682.72  4949.9 1682.60  4972.3 1681.24
  4978.7 1679.67  4998.9 1678.27  4999.4 1677.77  5015.5 1677.77  5016.0 1678.27
  5021.9 1679.46  5036.3 1683.65  5100.3 1687.80  5170.7 1690.95  5199.6 1691.97
  5234.8 1690.54  5270.0 1690.61  5284.4 1691.10  5298.8 1692.97  5306.0 1695.28
  5319.6 1696.10  5334.0 1696.51  5342.0 1695.82  5434.1 1697.41  5501.0 1697.96
#Mann=3,-1,0
  3801.6    0.05       0  4998.9    0.05       0  5016.0    0.05       0
Bank Sta=4998.9,5016
Exp/Cntr=0.3,0.1

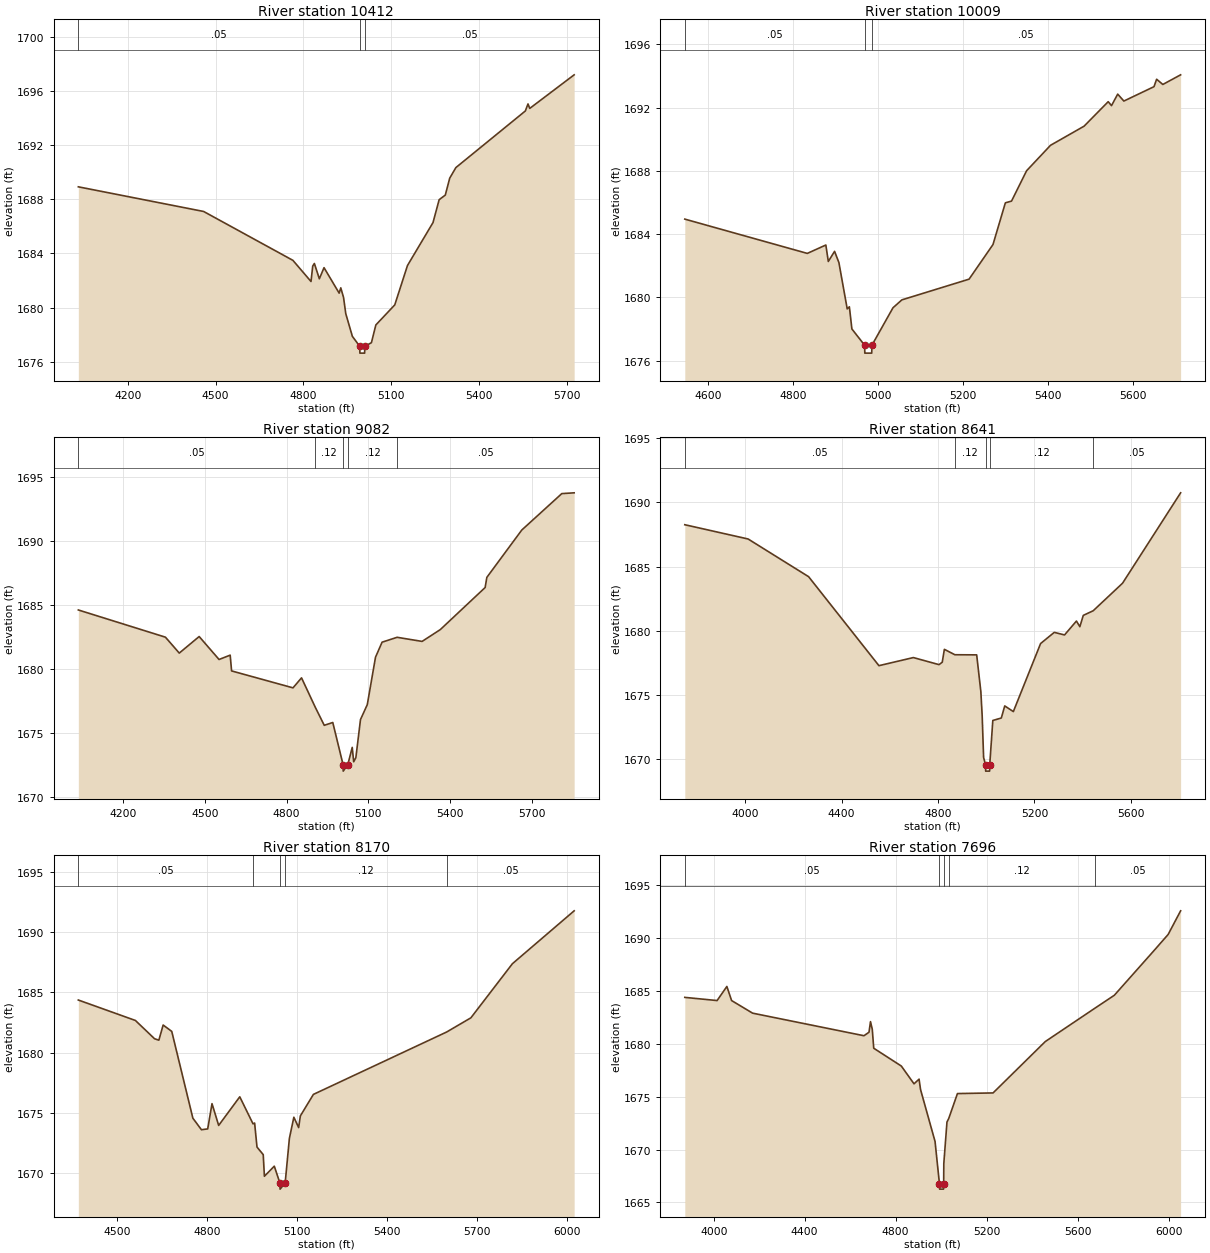
Type RM Length L Ch R = 1,10412,403,403,403
BEGIN DESCRIPTION:
Deadman 53 9.0
END DESCRIPTION:
XS GIS Cut Line= 3
      1619579.98      6890912.96      1620005.00      6891788.00
      1620405.00      6892388.00
#Sta/Elev= 30
  4031.1 1688.92  4459.2 1687.10  4764.2 1683.49  4826.0 1681.93  4831.9 1683.07
  4837.5 1683.26  4854.5 1682.13  4870.5 1682.95  4922.2 1681.07  4927.7 1681.46
  4937.2 1680.75  4944.7 1679.56  4967.3 1677.88  4992.5 1677.14  4993.0 1676.64
  5009.2 1676.64  5009.7 1677.14  5032.4 1677.41  5047.5 1678.72  5112.1 1680.20
  5155.6 1683.11  5242.8 1686.28  5263.8 1687.97  5284.8 1688.31  5299.9 1689.56
  5320.9 1690.34  5558.2 1694.52  5567.3 1695.04  5573.3 1694.71  5725.0 1697.19
#Mann=3,-1,0
  4031.1    0.05       0  4992.5    0.03       0  5009.7    0.05       0
Bank Sta=4992.5,5009.7
Exp/Cntr=0.3,0.1

Type RM Length L Ch R = 1,10009,927,927,927
BEGIN DESCRIPTION:
Mapping XS c7878733
END DESCRIPTION:
XS GIS Cut Line= 3
      1619509.17      6891433.84      1619592.50      6891822.72
      1620057.48      6892433.44
#Sta/Elev= 30
  4545.8 1684.95  4833.7 1682.78  4877.3 1683.31  4883.1 1682.27  4897.8 1682.91
  4908.0 1682.20  4927.5 1679.27  4932.6 1679.40  4938.5 1678.00  4968.4 1676.97
  4968.9 1676.47  4985.1 1676.47  4985.6 1676.97  5035.1 1679.34  5056.0 1679.84
  5213.9 1681.15  5270.1 1683.34  5299.2 1685.98  5313.7 1686.09  5349.1 1688.01
  5405.3 1689.62  5484.2 1690.83  5540.9 1692.38  5548.7 1692.13  5563.2 1692.86
  5577.7 1692.42  5648.5 1693.33  5654.7 1693.80  5669.3 1693.47  5711.1 1694.08
#Mann=3,-1,0
  4545.8    0.05       0  4968.4    0.03       0  4985.6    0.05       0
Bank Sta=4968.4,4985.6
Exp/Cntr=0.3,0.1

Type RM Length L Ch R = 1,9082,441,441,441
BEGIN DESCRIPTION:
Deadman 53 8.0
END DESCRIPTION:
XS GIS Cut Line= 3
      1619430.01      6891462.97      1619155.00      6892388.00
      1619454.99      6893187.96
#Sta/Elev= 30
  4035.8 1684.61  4355.4 1682.49  4406.2 1681.25  4479.2 1682.54  4552.2 1680.75
  4593.0 1681.09  4598.2 1679.86  4823.5 1678.54  4854.8 1679.32  4905.0 1677.04
  4938.2 1675.62  4969.5 1675.84  5007.3 1672.55  5007.8 1672.05  5024.6 1672.55
  5040.9 1673.90  5046.2 1672.78  5054.2 1673.10  5071.2 1676.07  5096.1 1677.23
  5126.3 1680.93  5150.4 1682.10  5205.6 1682.48  5297.2 1682.16  5364.0 1683.08
  5528.6 1686.36  5534.8 1687.15  5663.0 1690.84  5809.9 1693.68  5855.2 1693.74
#Mann=5,-1,0
  4035.8    0.05       0  4905.0    0.12       0  5007.3    0.07       0
  5024.6    0.12       0  5205.6    0.05       0
Bank Sta=5007.3,5024.6
Exp/Cntr=0.3,0.1

Type RM Length L Ch R = 1,8641,471,471,471
BEGIN DESCRIPTION:
Deadman 53 7.0
END DESCRIPTION:
XS GIS Cut Line= 3
      1618229.99      6891312.98      1618755.00      6892438.00
      1619304.98      6893037.98
#Sta/Elev= 30
  3750.4 1688.25  4012.9 1687.14  4263.6 1684.21  4555.2 1677.29  4697.9 1677.92
  4804.3 1677.37  4817.7 1677.56  4826.4 1678.56  4870.0 1678.14  4960.4 1678.13
  4977.7 1675.27  4983.2 1673.38  4989.1 1670.15  4997.1 1669.59  4997.6 1669.09
  5014.0 1669.09  5014.5 1669.59  5027.3 1673.03  5062.5 1673.22  5076.7 1674.16
  5112.4 1673.72  5225.3 1679.01  5282.0 1679.88  5324.6 1679.68  5373.9 1680.76
  5388.1 1680.32  5402.3 1681.20  5443.4 1681.56  5565.0 1683.70  5805.8 1690.73
#Mann=5,-1,0
  3750.4    0.05       0  4870.0    0.12       0  4997.1    0.07       0
  5014.5    0.12       0  5443.4    0.05       0
Bank Sta=4997.1,5014.5
Exp/Cntr=0.3,0.1

Type RM Length L Ch R = 1,8170,474,474,474
BEGIN DESCRIPTION:
Deadman 53 6.0
END DESCRIPTION:
XS GIS Cut Line= 3
      1618009.17      6892156.06      1618405.00      6892638.00
      1619304.98      6893137.99
#Sta/Elev= 30
  4369.9 1684.37  4560.2 1682.67  4624.0 1681.15  4638.4 1681.03  4652.7 1682.29
  4681.4 1681.76  4751.8 1674.54  4780.4 1673.58  4801.3 1673.65  4815.6 1675.75
  4837.8 1673.94  4908.2 1676.32  4952.4 1674.07  4957.7 1674.14  4965.6 1672.14
  4986.4 1671.51  4990.3 1669.71  5023.3 1670.55  5042.1 1669.14  5042.6 1668.64
  5059.5 1669.14  5073.6 1672.86  5088.5 1674.62  5104.5 1673.76  5110.2 1674.73
  5153.7 1676.52  5598.0 1681.71  5678.8 1682.89  5817.2 1687.39  6023.1 1691.79
#Mann=5,-1,0
  4369.9    0.05       0  4952.4    0.12       0  5042.1    0.07       0
  5059.5    0.12       0  5598.0    0.05       0
Bank Sta=5042.1,5059.5
Exp/Cntr=0.3,0.1

Type RM Length L Ch R = 1,7696,422,422,422
BEGIN DESCRIPTION:
Deadman 53 5.0
END DESCRIPTION:
XS GIS Cut Line= 3
      1617329.99      6892312.99      1618205.00      6893038.00
      1619205.02      6893338.01
#Sta/Elev= 30
  3872.8 1684.36  4014.8 1684.06  4057.8 1685.39  4078.6 1684.06  4171.1 1682.87
  4660.7 1680.74  4682.9 1681.07  4689.4 1682.07  4697.2 1681.35  4703.7 1679.56
  4824.9 1677.88  4880.8 1676.20  4903.0 1676.64  4909.5 1675.66  4973.3 1670.76
  4992.7 1666.76  4993.2 1666.26  5010.7 1666.26  5011.2 1666.76  5011.8 1668.67
  5025.7 1672.59  5033.5 1672.93  5071.8 1675.28  5228.4 1675.34  5458.1 1680.19
  5675.0 1683.32  5761.7 1684.56  5932.2 1688.68  5998.4 1690.30  6053.2 1692.53
#Mann=5,-1,0
  3872.8    0.05       0  4992.7    0.05       0  5011.2    0.05       0
  5033.5    0.12       0  5675.0    0.05       0
Bank Sta=4992.7,5011.2
Exp/Cntr=0.3,0.1

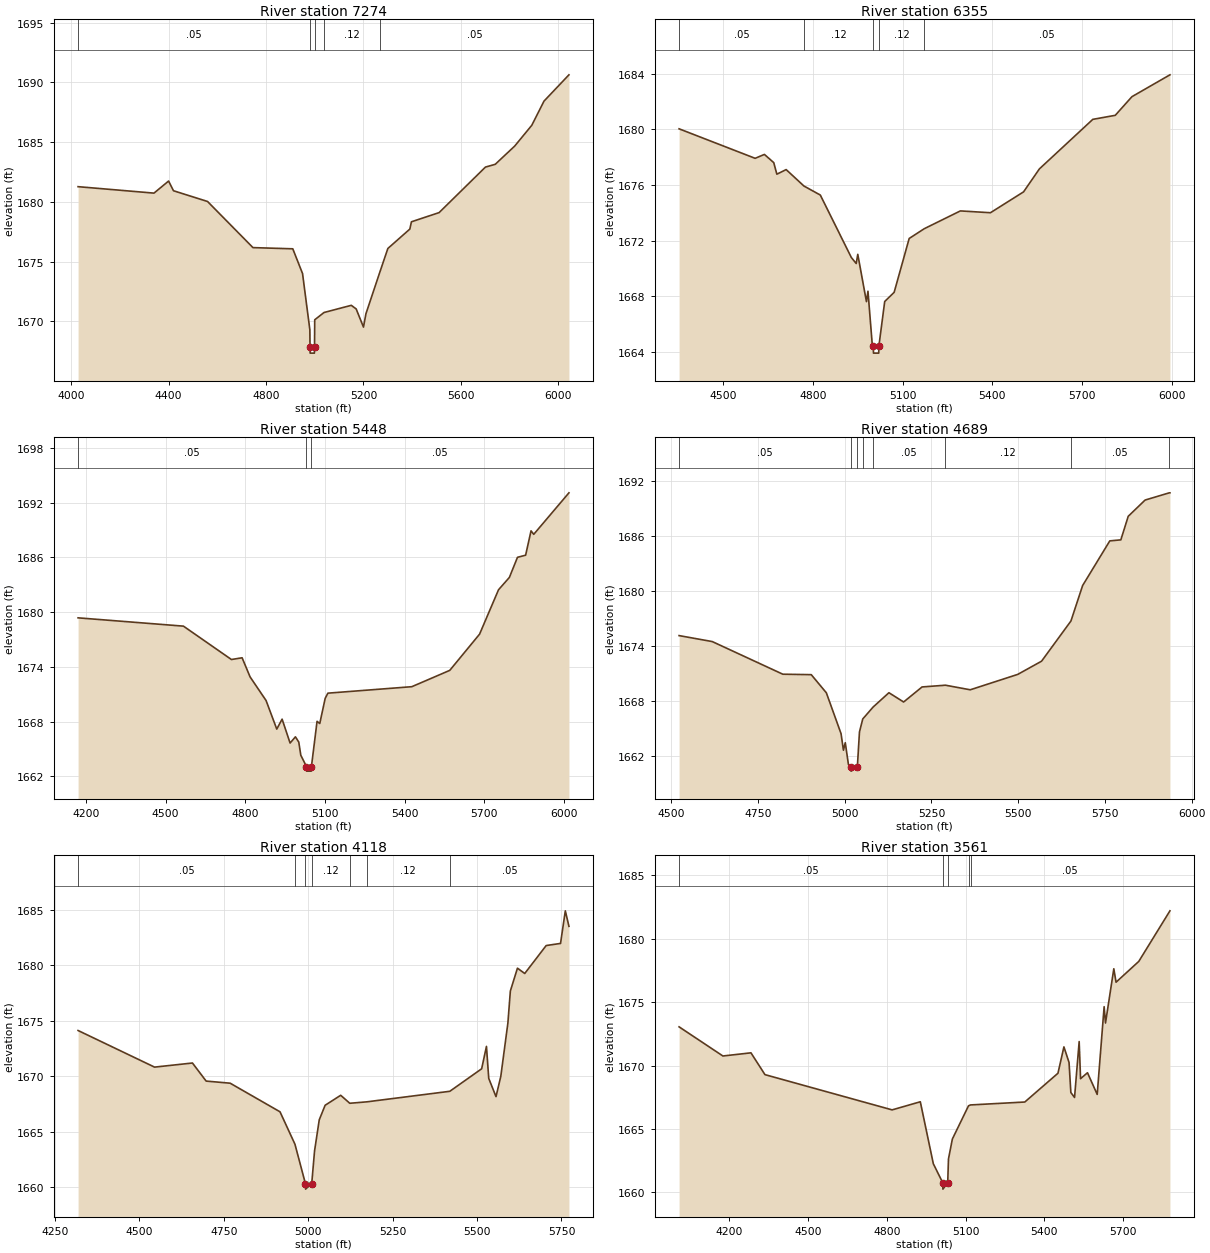
Type RM Length L Ch R = 1,7274,919,919,919
BEGIN DESCRIPTION:
Mapping XS 1c8317af
END DESCRIPTION:
XS GIS Cut Line= 3
      1617113.38      6893343.56      1618141.11      6893371.33
      1619127.22      6893433.83
#Sta/Elev= 30
  4027.9 1681.28  4339.6 1680.74  4399.7 1681.75  4419.7 1680.94  4559.7 1680.04
  4746.2 1676.18  4909.8 1676.08  4949.9 1674.01  4979.9 1669.31  4980.6 1667.85
  4981.1 1667.35  4998.6 1667.35  4999.1 1667.85  4999.9 1670.14  5038.1 1670.75
  5150.1 1671.35  5170.1 1671.05  5200.2 1669.53  5210.2 1670.64  5268.4 1674.19
  5300.4 1676.11  5390.6 1677.73  5397.1 1678.34  5510.8 1679.11  5701.2 1682.92
  5741.3 1683.15  5821.4 1684.68  5891.6 1686.42  5941.7 1688.44  6044.1 1690.64
#Mann=5,-1,0
  4027.9    0.05       0  4980.6    0.05       0  4999.1    0.05       0
  5038.1    0.12       0  5268.4    0.05       0
Bank Sta=4980.6,4999.1
Exp/Cntr=0.3,0.1

Type RM Length L Ch R = 1,6355,907,907,907
BEGIN DESCRIPTION:
Deadman 53 4.0
END DESCRIPTION:
XS GIS Cut Line= 3
      1617480.03      6893813.01      1618105.00      6893988.00
      1619091.24      6893871.48
#Sta/Elev= 30
  4351.8 1680.04  4606.2 1677.92  4637.3 1678.20  4668.5 1677.61  4678.9 1676.78
  4710.0 1677.11  4769.4 1675.93  4824.3 1675.28  4928.1 1670.79  4944.4 1670.36
  4949.6 1671.02  4978.6 1667.62  4983.7 1668.37  4998.2 1664.49  5001.6 1664.42
  5002.1 1663.92  5019.7 1663.92  5020.2 1664.42  5039.7 1667.63  5071.3 1668.29
  5121.6 1672.16  5171.9 1672.86  5292.8 1674.14  5393.5 1674.01  5504.3 1675.51
  5557.2 1677.16  5735.9 1680.72  5811.0 1681.01  5866.8 1682.35  5993.9 1683.92
#Mann=5,-1,0
  4351.8    0.05       0  4769.4    0.12       0  5001.6    0.07       0
  5020.2    0.12       0  5171.9    0.05       0
Bank Sta=5001.6,5020.2
Exp/Cntr=0.3,0.1

Type RM Length L Ch R = 1,5448,759,759,759
BEGIN DESCRIPTION:
Deadman 53 3.0
END DESCRIPTION:
XS GIS Cut Line= 3
      1617429.97      6894663.00      1618255.00      6894738.00
      1619254.97      6894538.01
#Sta/Elev= 30
  4170.7 1679.38  4567.4 1678.47  4748.1 1674.81  4788.3 1675.00  4818.4 1672.90
  4878.6 1670.31  4918.8 1667.18  4938.9 1668.27  4969.0 1665.65  4989.1 1666.33
  5001.7 1665.75  5009.3 1664.31  5030.6 1663.07  5031.1 1662.57  5048.8 1662.57
  5049.3 1663.07  5070.5 1668.03  5080.7 1667.79  5101.1 1670.55  5111.3 1671.12
  5427.4 1671.83  5570.2 1673.62  5682.4 1677.59  5753.8 1682.46  5794.6 1683.81
  5825.2 1686.02  5855.8 1686.25  5876.2 1688.92  5886.4 1688.54  6018.9 1693.09
#Mann=3,-1,0
  4170.7    0.05       0  5030.6    0.05       0  5049.3    0.05       0
Bank Sta=5030.6,5049.3
Exp/Cntr=0.3,0.1

Type RM Length L Ch R = 1,4689,571,571,571
BEGIN DESCRIPTION:
Mapping XS a7239120
END DESCRIPTION:
XS GIS Cut Line= 2
      1617904.99      6895461.61      1619238.34      6894989.39
#Sta/Elev= 30
  4522.9 1675.13  4618.4 1674.48  4821.8 1670.92  4903.8 1670.87  4947.3 1668.89
  4989.7 1664.43  4996.5 1662.63  5001.8 1663.45  5010.9 1661.08  5018.0 1660.85
  5018.5 1660.35  5036.7 1660.85  5042.7 1664.62  5052.2 1666.04  5082.1 1667.34
  5127.6 1668.90  5170.0 1667.89  5223.1 1669.53  5290.5 1669.72  5361.9 1669.22
  5498.9 1670.90  5567.5 1672.34  5652.1 1676.72  5685.8 1680.59  5764.1 1685.46
  5795.9 1685.57  5817.2 1688.14  5865.8 1689.91  5935.5 1690.70  5937.4 1690.70
#Mann=8,-1,0
  4522.9    0.05       0  5018.0    0.05       0  5036.7    0.05       0
  5052.2    0.12       0  5082.1    0.05       0  5290.5    0.12       0
  5652.1    0.05       0  5935.5    0.12       0
Bank Sta=5018,5036.7
Exp/Cntr=0.3,0.1

Type RM Length L Ch R = 1,4118,557,557,557
BEGIN DESCRIPTION:
Mapping XS 7f887c0e
END DESCRIPTION:
XS GIS Cut Line= 4
      1617941.45      6895772.86      1618391.76      6895852.32
      1618823.11      6895704.76      1619220.23      6895337.89
#Sta/Elev= 30
  4318.4 1674.12  4544.9 1670.82  4657.1 1671.19  4697.7 1669.56  4768.8 1669.37
  4916.5 1666.79  4960.7 1663.87  4991.7 1660.32  4992.2 1659.82  5010.4 1660.32
  5018.8 1663.27  5032.7 1666.07  5050.1 1667.38  5096.2 1668.28  5123.1 1667.56
  5173.8 1667.69  5419.4 1668.64  5513.7 1670.67  5527.9 1672.69  5534.7 1669.80
  5556.2 1668.16  5570.4 1669.99  5591.4 1674.80  5598.7 1677.68  5619.7 1679.74
  5641.3 1679.26  5704.8 1681.78  5747.3 1681.97  5761.5 1684.91  5772.2 1683.51
#Mann=7,-1,0
  4318.4    0.05       0  4960.7    0.12       0  4991.7    0.07       0
  5010.4    0.12       0  5123.1    0.05       0  5173.8    0.12       0
  5419.4    0.05       0
Bank Sta=4991.7,5010.4
Exp/Cntr=0.3,0.1

Type RM Length L Ch R = 1,3561,678,678,678
BEGIN DESCRIPTION:
Mapping XS f2693bd4
END DESCRIPTION:
XS GIS Cut Line= 4
      1618005.81      6895969.62      1618736.08      6896268.54
      1619027.43      6896079.35      1619258.26      6895383.09
#Sta/Elev= 30
  4008.5 1673.06  4175.5 1670.76  4282.3 1671.01  4335.7 1669.29  4820.1 1666.51
  4927.5 1667.15  4977.1 1662.26  5013.1 1660.76  5013.6 1660.26  5031.9 1660.76
  5034.8 1662.64  5049.6 1664.21  5111.1 1666.83  5118.8 1666.90  5325.5 1667.13
  5451.9 1669.40  5474.6 1671.48  5494.1 1670.25  5501.0 1667.88  5515.1 1667.49
  5532.7 1671.90  5538.0 1668.97  5564.4 1669.44  5601.4 1667.73  5627.8 1674.65
  5633.0 1673.36  5664.7 1677.64  5673.2 1676.58  5759.8 1678.22  5878.5 1682.21
#Mann=5,-1,0
  4008.5    0.05       0  5013.1    0.05       0  5031.9    0.05       0
  5111.1    0.12       0  5118.8    0.05       0
Bank Sta=5013.1,5031.9
Exp/Cntr=0.3,0.1

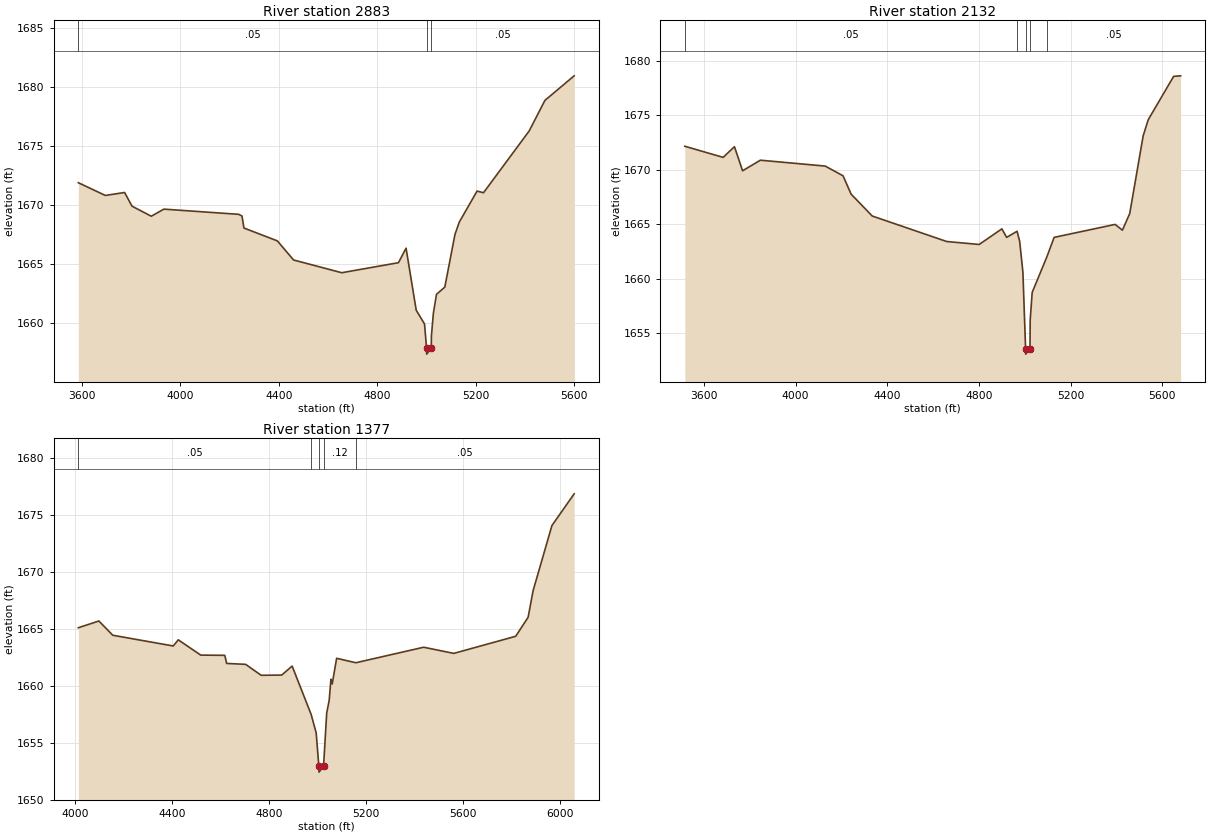
Type RM Length L Ch R = 1,2883,751,751,751
BEGIN DESCRIPTION:
Mapping XS b8e9898e
END DESCRIPTION:
XS GIS Cut Line= 4
      1618089.09      6896102.08      1619061.49      6896741.51
      1619530.68      6896624.22      1619814.44      6896389.64
#Sta/Elev= 30
  3584.9 1671.92  3694.7 1670.84  3773.0 1671.09  3803.2 1669.93  3881.5 1669.08
  3932.7 1669.68  4237.0 1669.24  4250.2 1669.10  4258.1 1668.08  4393.9 1666.99
  4459.9 1665.37  4655.8 1664.29  4886.3 1665.14  4917.2 1666.37  4958.5 1661.11
  4992.3 1659.94  5000.5 1657.89  5001.0 1657.39  5019.6 1657.89  5020.3 1658.95
  5028.3 1660.87  5040.9 1662.46  5074.7 1663.07  5116.0 1667.54  5133.7 1668.59
  5205.9 1671.21  5232.0 1671.07  5417.8 1676.31  5481.7 1678.90  5600.5 1680.98
#Mann=3,-1,0
  3584.9    0.05       0  5000.5    0.05       0  5019.6    0.05       0
Bank Sta=5000.5,5019.6
Exp/Cntr=0.3,0.1

Type RM Length L Ch R = 1,2132,755,755,755
BEGIN DESCRIPTION:
Deadman 53 2.0
END DESCRIPTION:
XS GIS Cut Line= 3
      1618081.51      6896155.05      1619152.45      6897181.91
      1619799.29      6897392.31
#Sta/Elev= 30
  3516.3 1672.16  3683.6 1671.14  3733.0 1672.12  3768.5 1669.91  3846.2 1670.88
  4129.2 1670.34  4206.9 1669.45  4242.1 1667.77  4334.3 1665.76  4659.5 1663.42
  4801.0 1663.15  4900.0 1664.58  4921.1 1663.80  4966.4 1664.36  4977.7 1663.45
  4991.9 1660.60  5003.6 1653.59  5004.1 1653.09  5022.8 1653.59  5023.7 1656.22
  5032.4 1658.75  5096.2 1662.00  5128.2 1663.80  5394.2 1664.99  5426.2 1664.46
  5458.1 1665.99  5516.7 1673.11  5539.0 1674.60  5649.7 1678.57  5680.2 1678.62
#Mann=5,-1,0
  3516.3    0.05       0  4966.4    0.12       0  5003.6    0.07       0
  5022.8    0.12       0  5096.2    0.05       0
Bank Sta=5003.6,5022.8
Exp/Cntr=0.3,0.1

Type RM Length L Ch R = 1,1377,0,0,0
BEGIN DESCRIPTION:
Deadman 53 1.0
END DESCRIPTION:
XS GIS Cut Line= 3
      1618129.98      6896912.98      1618768.05      6897691.16
      1619780.02      6897463.00
#Sta/Elev= 30
  4013.6 1665.10  4098.3 1665.69  4155.7 1664.44  4404.8 1663.50  4425.6 1664.04
  4518.1 1662.70  4617.2 1662.68  4625.1 1661.97  4703.3 1661.89  4767.2 1660.93
  4851.9 1660.95  4894.9 1661.74  4973.2 1657.50  4994.0 1655.88  5005.1 1652.94
  5005.6 1652.44  5024.3 1652.94  5037.3 1657.61  5047.6 1658.74  5054.8 1660.59
  5060.0 1660.17  5078.3 1662.42  5157.5 1662.03  5437.1 1663.39  5561.2 1662.85
  5816.4 1664.35  5867.6 1666.02  5888.1 1668.35  5965.7 1674.06  6057.3 1676.84
#Mann=5,-1,0
  4013.6    0.05       0  4973.2    0.12       0  5005.1    0.07       0
  5024.3    0.12       0  5157.5    0.05       0
Bank Sta=5005.1,5024.3
Exp/Cntr=0.3,0.1

Chan Stop Cuts=-1