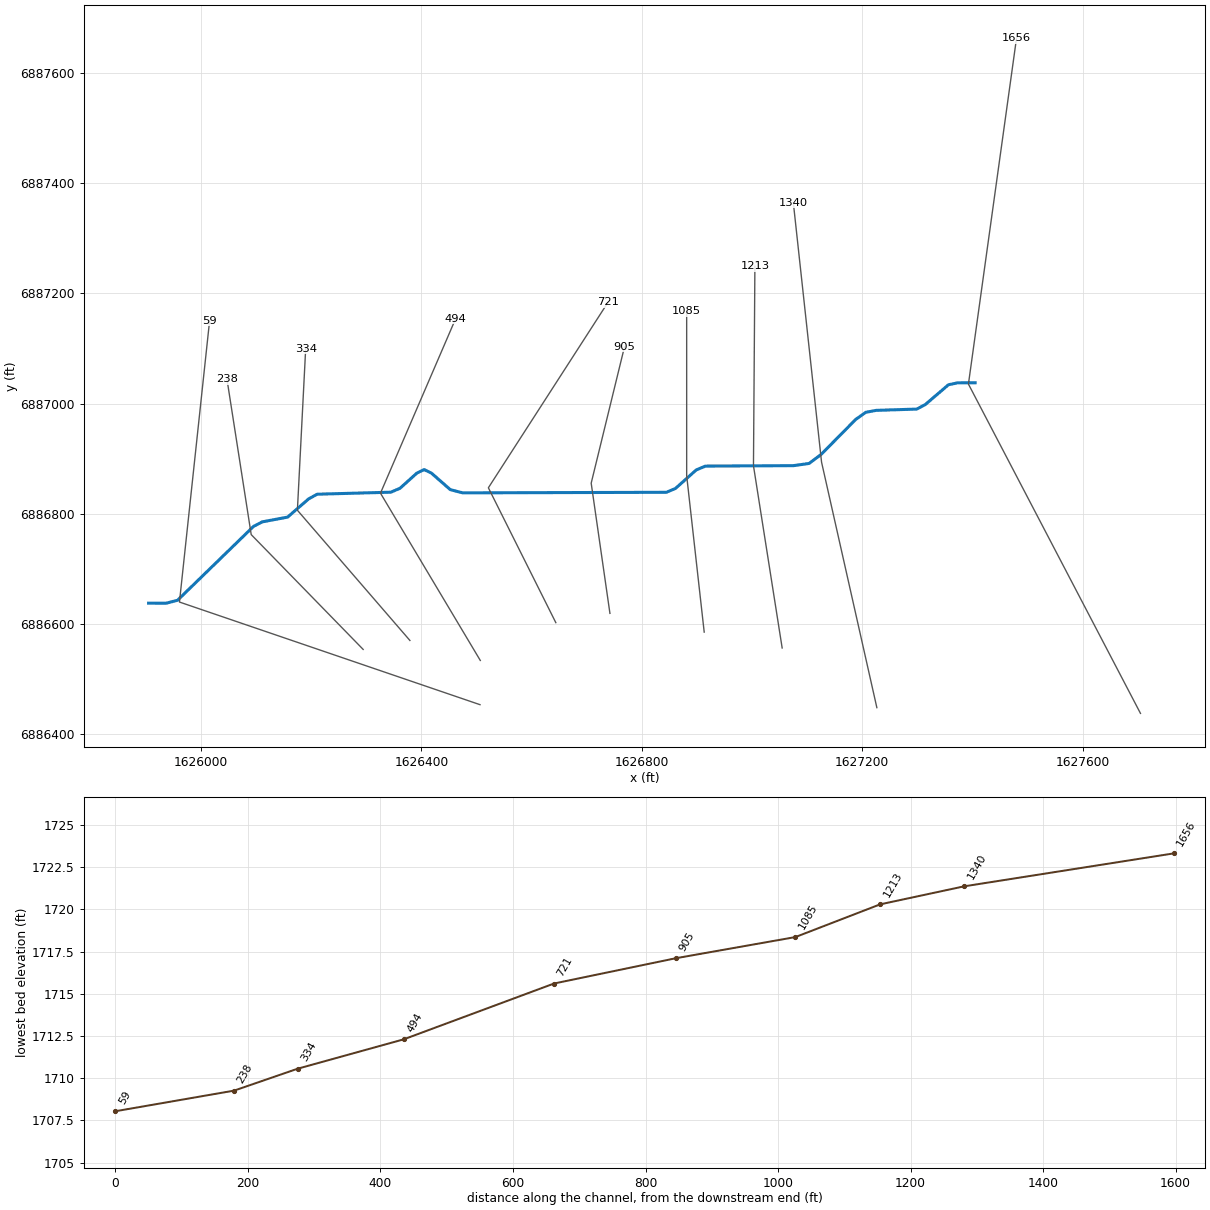
--- Deadman 55.prj (project) ---

Proj Title=Deadman 55 Base Level Engineering
Current Plan=p01
Default Exp/Contr=0.3,0.1
English Units
Geom File=g01
Flow File=f01
Plan File=p01
BEGIN DESCRIPTION:
Deadman 55
END DESCRIPTION:

--- Deadman 55.p01 (plan) ---

Plan Title=Multiple Run
Short Identifier=Multiple
Geom File=g01
Flow File=f01
Subcritical Flow
K Sum by GR= 0
Std Step Tol= 0.01
Critical Tol= 0.01
Num of Std Step Trials= 20
Max Error Tol= 0.3
Flow Tol Ratio= 0.001
Split Flow NTrial= 30
Split Flow Tol= 0.02
Split Flow Ratio= 0.02
Log Output Level= 0
Friction Slope Method= 1
Unsteady Friction Slope Method= 2
Unsteady Bridges Friction Slope Method= 1
Parabolic Critical Depth
Global Vel Dist=  1 , 1 , 1
Global Log Level= 0
CheckData=True
Encroach Param= -1, 0, 0, 0
BEGIN DESCRIPTION:
Multiple Run
END DESCRIPTION:

--- Deadman 55.f01 (steady flow) ---

Flow Title=Multiple
Number of Profiles=7
Profile Names=10-year,25-year,50-year,1pct_min,100-year,1pct_plu,500-year
River Rch & RM= Deadman 55,Reach-1,1656
     239     328     401     245     488     974     730
River Rch & RM= Deadman 55,Reach-1,1340
     248     342     419     256     511    1019     767
Boundary for River Rch & Prof#=Deadman 55,Reach-1,1
Up Type=0
Dn Type=3
Dn Slope=0.007
Boundary for River Rch & Prof#=Deadman 55,Reach-1,2
Up Type=0
Dn Type=3
Dn Slope=0.007
Boundary for River Rch & Prof#=Deadman 55,Reach-1,3
Up Type=0
Dn Type=3
Dn Slope=0.007
Boundary for River Rch & Prof#=Deadman 55,Reach-1,4
Up Type=0
Dn Type=3
Dn Slope=0.007
Boundary for River Rch & Prof#=Deadman 55,Reach-1,5
Up Type=0
Dn Type=3
Dn Slope=0.007
Boundary for River Rch & Prof#=Deadman 55,Reach-1,6
Up Type=0
Dn Type=3
Dn Slope=0.007
Boundary for River Rch & Prof#=Deadman 55,Reach-1,7
Up Type=0
Dn Type=3
Dn Slope=0.007

--- Deadman 55.g01 (geometry) ---

Geom Title=Existing Conditions

River Reach=Deadman 55,Reach-1
Reach XY= 30
      1627405.00      6887038.00      1627373.20      6887037.88
      1627356.51      6887034.36      1627314.75      6886998.62
      1627299.08      6886990.23      1627225.05      6886987.88
      1627206.50      6886984.38      1627188.26      6886971.51
      1627125.15      6886907.65      1627103.53      6886891.55
      1627075.18      6886887.57      1626915.51      6886886.78
      1626898.94      6886879.86      1626861.06      6886846.14
      1626844.50      6886839.22      1626474.98      6886838.18
      1626452.55      6886844.02      1626418.21      6886874.05
      1626405.00      6886880.44      1626391.79      6886874.05
      1626361.18      6886846.46      1626344.56      6886839.40
      1626210.93      6886835.75      1626195.33      6886827.20
      1626157.17      6886794.14      1626111.03      6886785.50
      1626095.32      6886777.24      1625957.52      6886643.31
      1625936.88      6886637.93      1625905.00      6886638.00

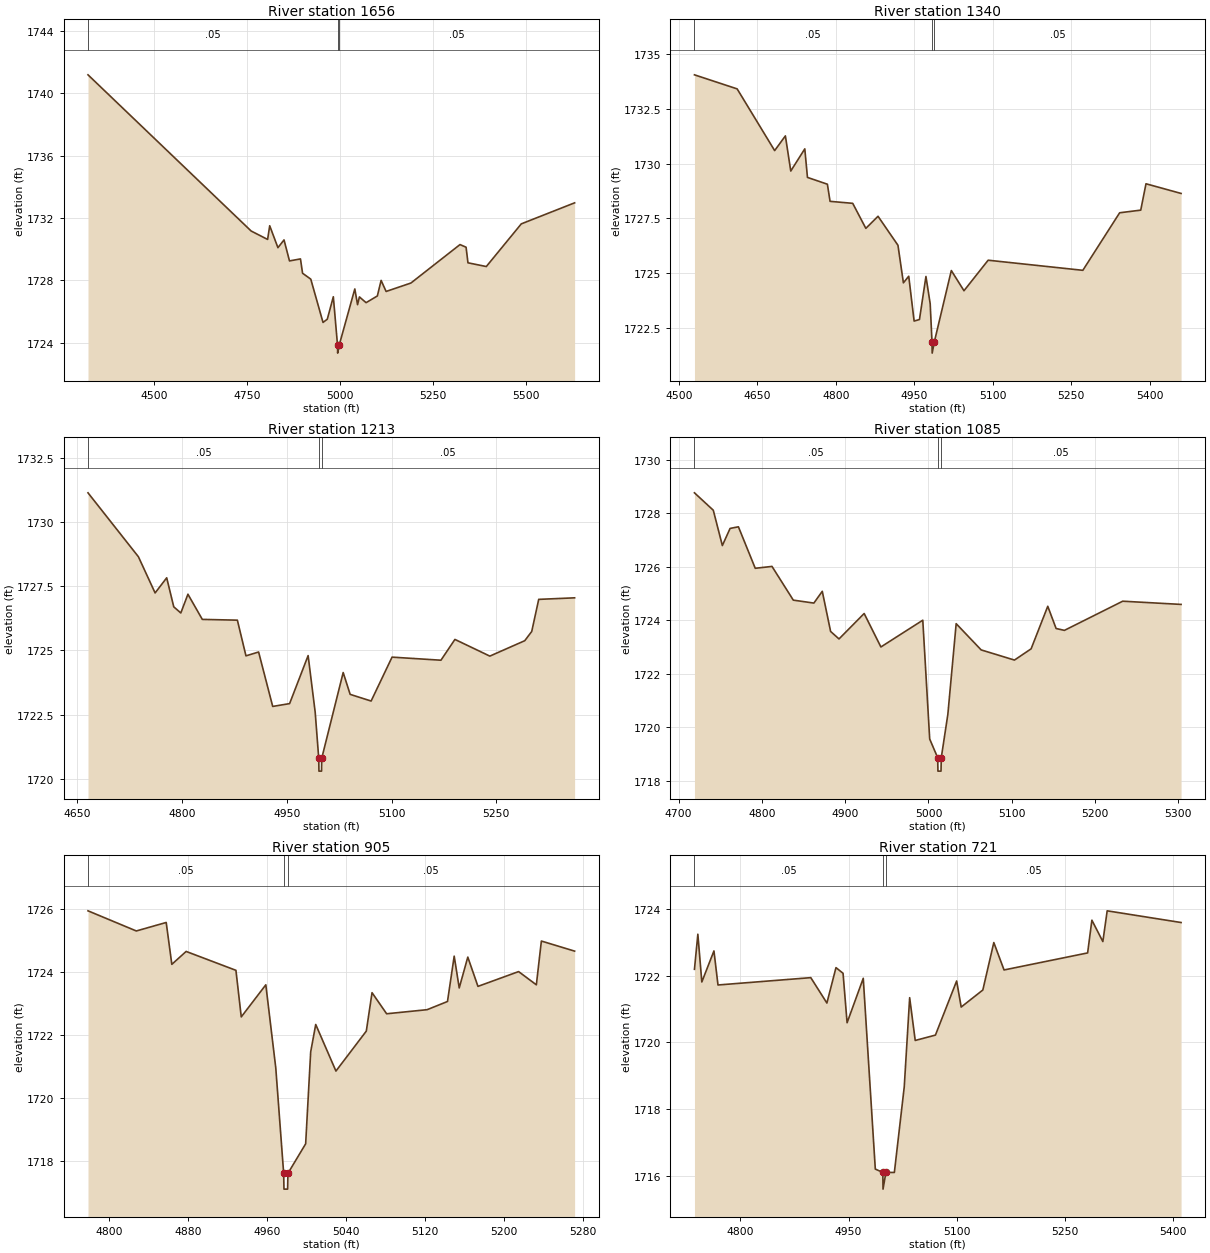
Type RM Length L Ch R = 1,1656,316,316,316
BEGIN DESCRIPTION:
Deadman 55 2.0
END DESCRIPTION:
XS GIS Cut Line= 3
      1627704.99      6886438.02      1627392.77      6887035.60
      1627480.01      6887663.04
#Sta/Elev= 30
  4323.4 1741.19  4761.9 1731.16  4806.1 1730.62  4811.7 1731.50  4833.8 1730.09
  4850.2 1730.59  4864.9 1729.24  4894.4 1729.37  4900.0 1728.45  4922.1 1728.07
  4955.0 1725.29  4966.5 1725.50  4982.7 1726.94  4994.0 1723.82  4994.3 1723.32
  4998.3 1723.82  5040.4 1727.44  5047.8 1726.43  5052.8 1726.93  5070.7 1726.56
  5101.0 1726.99  5111.1 1727.99  5124.5 1727.28  5191.1 1727.82  5323.1 1730.29
  5339.4 1730.12  5344.5 1729.12  5393.8 1728.88  5487.8 1731.62  5631.1 1732.97
#Mann=3,-1,0
  4323.4    0.05       0  4994.0    0.05       0  4998.3    0.05       0
Bank Sta=4994,4998.3
Exp/Cntr=0.3,0.1

Type RM Length L Ch R = 1,1340,127,127,127
BEGIN DESCRIPTION:
Mapping XS b4e46903
END DESCRIPTION:
XS GIS Cut Line= 3
      1627226.59      6886448.41      1627126.23      6886893.93
      1627075.01      6887364.67
#Sta/Elev= 30
  4529.8 1734.04  4611.4 1733.40  4683.1 1730.59  4703.6 1731.26  4713.9 1729.66
  4740.7 1730.67  4745.8 1729.37  4783.9 1729.06  4789.0 1728.28  4832.3 1728.19
  4857.4 1727.05  4880.7 1727.60  4918.8 1726.28  4929.2 1724.57  4939.4 1724.87
  4949.7 1722.83  4959.9 1722.90  4972.3 1724.86  4980.4 1723.62  4983.9 1721.87
  4984.2 1721.37  4988.2 1721.87  5020.8 1725.13  5045.0 1724.21  5091.2 1725.60
  5272.2 1725.14  5342.6 1727.76  5382.9 1727.88  5392.9 1729.08  5460.0 1728.64
#Mann=3,-1,0
  4529.8    0.05       0  4983.9    0.05       0  4988.2    0.05       0
Bank Sta=4983.9,4988.2
Exp/Cntr=0.3,0.1

Type RM Length L Ch R = 1,1213,128,128,128
BEGIN DESCRIPTION:
Mapping XS 363bd879
END DESCRIPTION:
XS GIS Cut Line= 3
      1627054.74      6886556.69      1627002.66      6886887.44
      1627005.26      6887249.40
#Sta/Elev= 30
  4665.4 1731.14  4737.6 1728.65  4761.5 1727.24  4778.1 1727.83  4788.2 1726.70
  4798.3 1726.46  4808.5 1727.19  4829.1 1726.21  4879.3 1726.18  4891.6 1724.79
  4909.7 1724.94  4929.9 1722.82  4954.1 1722.93  4980.6 1724.80  4990.7 1722.60
  4995.8 1720.80  4996.1 1720.30  4999.8 1720.30  5000.1 1720.80  5030.8 1724.14
  5040.8 1723.29  5070.8 1723.03  5100.8 1724.74  5170.8 1724.62  5190.8 1725.43
  5240.8 1724.78  5290.8 1725.38  5300.8 1725.74  5310.8 1726.99  5362.2 1727.05
#Mann=3,-1,0
  4665.4    0.05       0  4995.8    0.05       0  5000.1    0.05       0
Bank Sta=4995.8,5000.1
Exp/Cntr=0.3,0.1

Type RM Length L Ch R = 1,1085,180,180,180
BEGIN DESCRIPTION:
Mapping XS 29af47ef
END DESCRIPTION:
XS GIS Cut Line= 3
      1626913.26      6886585.50      1626881.44      6886869.45
      1626881.44      6887168.12
#Sta/Elev= 30
  4719.0 1728.76  4741.6 1728.11  4752.5 1726.79  4761.8 1727.43  4771.8 1727.49
  4792.0 1725.94  4812.1 1726.01  4837.7 1724.75  4862.4 1724.64  4872.5 1725.08
  4882.5 1723.58  4892.6 1723.30  4922.8 1724.25  4942.9 1723.00  4993.2 1724.00
  5001.5 1719.56  5011.1 1718.86  5011.4 1718.36  5015.1 1718.36  5015.4 1718.86
  5023.3 1720.48  5033.3 1723.87  5063.3 1722.89  5103.3 1722.51  5123.3 1722.93
  5143.3 1724.52  5153.3 1723.69  5163.3 1723.62  5233.3 1724.71  5303.4 1724.59
#Mann=3,-1,0
  4719.0    0.05       0  5011.1    0.05       0  5015.4    0.05       0
Bank Sta=5011.1,5015.4
Exp/Cntr=0.3,0.1

Type RM Length L Ch R = 1,905,184,184,184
BEGIN DESCRIPTION:
Mapping XS 0ed28bde
END DESCRIPTION:
XS GIS Cut Line= 3
      1626742.19      6886619.51      1626708.17      6886855.80
      1626768.60      6887103.19
#Sta/Elev= 30
  4778.4 1725.95  4827.4 1725.31  4857.7 1725.58  4863.4 1724.25  4877.9 1724.66
  4928.4 1724.06  4933.8 1722.58  4958.7 1723.60  4968.8 1720.96  4976.8 1717.61
  4977.1 1717.11  4980.8 1717.11  4981.1 1717.61  4999.1 1718.55  5004.2 1721.47
  5009.3 1722.34  5029.8 1720.86  5060.6 1722.13  5066.4 1723.35  5081.2 1722.68
  5122.3 1722.81  5142.9 1723.07  5149.7 1724.51  5154.8 1723.50  5163.5 1724.48
  5173.8 1723.55  5215.0 1724.02  5233.0 1723.60  5238.1 1724.99  5271.8 1724.67
#Mann=3,-1,0
  4778.4    0.05       0  4976.8    0.05       0  4981.1    0.05       0
Bank Sta=4976.8,4981.1
Exp/Cntr=0.3,0.1

Type RM Length L Ch R = 1,721,227,227,227
BEGIN DESCRIPTION:
Mapping XS 448ca273
END DESCRIPTION:
XS GIS Cut Line= 3
      1626643.99      6886602.65      1626521.60      6886847.42
      1626738.74      6887184.11
#Sta/Elev= 30
  4736.5 1722.19  4741.2 1723.24  4746.7 1721.81  4763.5 1722.74  4769.1 1721.72
  4897.7 1721.94  4920.0 1721.18  4932.6 1722.24  4942.4 1722.07  4948.0 1720.59
  4970.4 1721.92  4987.1 1716.21  4997.5 1716.11  4997.8 1715.61  5001.8 1716.11
  5013.5 1716.11  5027.2 1718.67  5034.7 1721.34  5042.4 1720.06  5070.4 1720.22
  5099.8 1721.84  5106.1 1721.06  5136.1 1721.57  5151.3 1722.99  5165.5 1722.17
  5281.3 1722.68  5287.2 1723.66  5302.4 1723.02  5308.4 1723.94  5410.8 1723.59
#Mann=3,-1,0
  4736.5    0.05       0  4997.5    0.05       0  5001.8    0.05       0
Bank Sta=4997.5,5001.8
Exp/Cntr=0.3,0.1

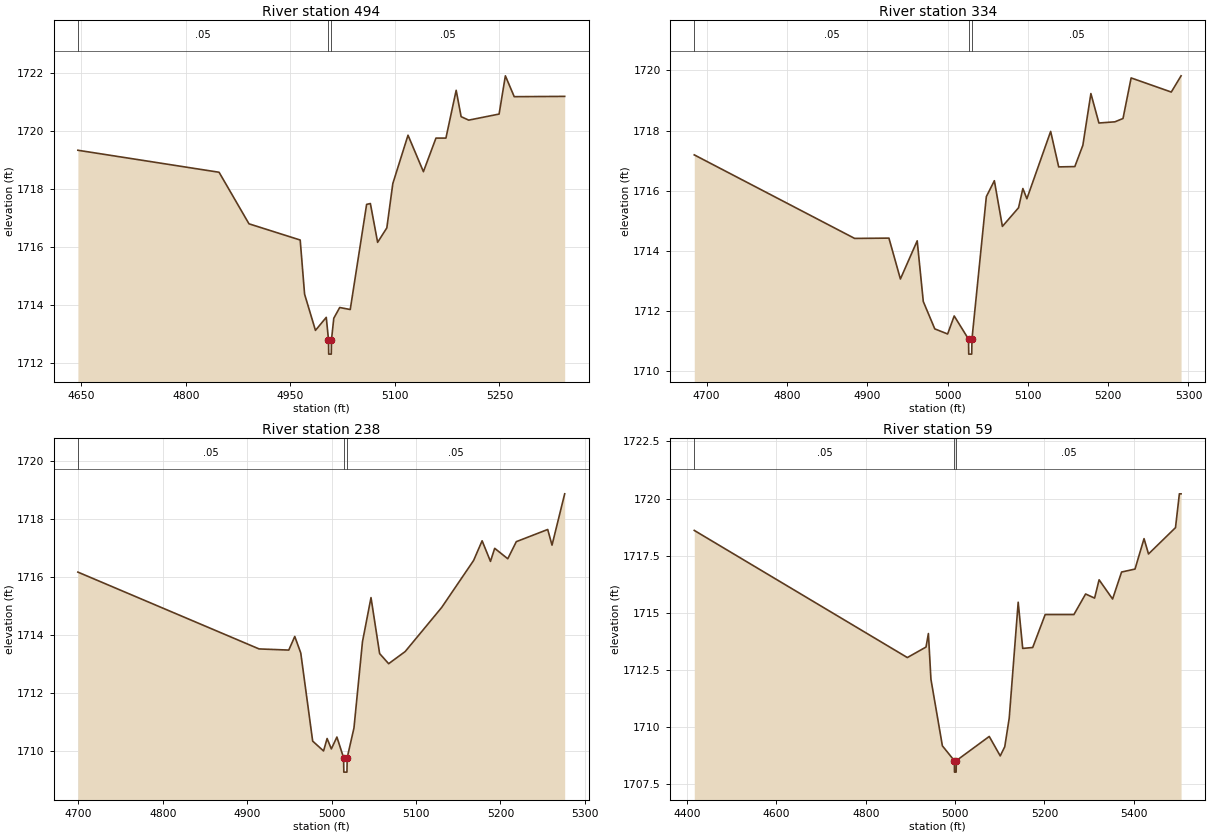
Type RM Length L Ch R = 1,494,160,160,160
BEGIN DESCRIPTION:
Mapping XS d19373f0
END DESCRIPTION:
XS GIS Cut Line= 3
      1626506.93      6886534.06      1626325.77      6886837.63
      1626462.25      6887154.46
#Sta/Elev= 30
  4645.1 1719.34  4847.7 1718.58  4890.6 1716.80  4964.1 1716.24  4970.4 1714.37
  4986.0 1713.12  5001.5 1713.57  5004.7 1712.80  5005.0 1712.30  5008.7 1712.30
  5009.0 1712.80  5012.3 1713.54  5020.8 1713.91  5035.9 1713.84  5059.4 1717.47
  5064.8 1717.50  5075.2 1716.16  5088.4 1716.66  5097.0 1718.19  5118.8 1719.86
  5140.9 1718.60  5158.9 1719.76  5173.2 1719.76  5187.9 1721.41  5195.0 1720.50
  5205.9 1720.38  5249.5 1720.59  5258.5 1721.91  5271.2 1721.19  5343.6 1721.20
#Mann=3,-1,0
  4645.1    0.05       0  5004.7    0.05       0  5009.0    0.05       0
Bank Sta=5004.7,5009
Exp/Cntr=0.3,0.1

Type RM Length L Ch R = 1,334,96,96,96
BEGIN DESCRIPTION:
Mapping XS 12552942
END DESCRIPTION:
XS GIS Cut Line= 3
      1626379.19      6886570.33      1626175.02      6886806.64
      1626190.07      6887100.16
#Sta/Elev= 30
  4684.6 1717.19  4884.3 1714.41  4927.0 1714.42  4941.3 1713.06  4962.2 1714.33
  4969.8 1712.31  4984.1 1711.40  5000.1 1711.23  5008.3 1711.83  5026.1 1711.06
  5026.4 1710.56  5030.1 1710.56  5030.4 1711.06  5048.3 1715.80  5058.3 1716.33
  5068.3 1714.81  5088.4 1715.43  5093.8 1716.07  5098.8 1715.73  5128.4 1717.97
  5138.4 1716.79  5158.5 1716.80  5168.5 1717.51  5178.5 1719.23  5188.5 1718.25
  5208.5 1718.29  5218.5 1718.40  5228.6 1719.75  5278.6 1719.28  5290.8 1719.82
#Mann=3,-1,0
  4684.6    0.05       0  5026.1    0.05       0  5030.4    0.05       0
Bank Sta=5026.1,5030.4
Exp/Cntr=0.3,0.1

Type RM Length L Ch R = 1,238,179,179,179
BEGIN DESCRIPTION:
Mapping XS e45fe6aa
END DESCRIPTION:
XS GIS Cut Line= 3
      1626294.36      6886554.08      1626091.20      6886762.44
      1626047.19      6887044.62
#Sta/Elev= 30
  4699.5 1716.16  4914.1 1713.51  4949.3 1713.47  4956.4 1713.94  4963.5 1713.37
  4977.6 1710.33  4990.5 1709.99  4994.7 1710.42  4999.7 1710.06  5006.3 1710.47
  5014.2 1709.76  5014.5 1709.26  5018.2 1709.26  5018.5 1709.76  5026.5 1710.78
  5036.6 1713.76  5046.7 1715.28  5056.9 1713.35  5067.6 1713.00  5087.2 1713.42
  5130.4 1714.94  5168.2 1716.56  5178.3 1717.24  5188.2 1716.53  5193.2 1716.98
  5208.7 1716.62  5218.8 1717.21  5256.0 1717.63  5261.1 1717.09  5276.1 1718.86
#Mann=3,-1,0
  4699.5    0.05       0  5014.2    0.05       0  5018.5    0.05       0
Bank Sta=5014.2,5018.5
Exp/Cntr=0.3,0.1

Type RM Length L Ch R = 1,59,0,0,0
BEGIN DESCRIPTION:
Deadman 55 1.0
END DESCRIPTION:
XS GIS Cut Line= 3
      1626506.42      6886453.80      1625960.99      6886640.05
      1626015.68      6887150.48
#Sta/Elev= 30
  4416.2 1718.61  4893.2 1713.05  4935.0 1713.51  4940.3 1714.10  4946.0 1712.10
  4971.6 1709.19  4998.4 1708.54  4998.7 1708.04  5002.4 1708.04  5002.7 1708.54
  5076.5 1709.60  5101.1 1708.75  5111.2 1709.15  5121.2 1710.40  5141.3 1715.47
  5151.4 1713.45  5173.8 1713.49  5201.7 1714.93  5266.0 1714.93  5292.2 1715.83
  5312.3 1715.65  5322.4 1716.45  5352.6 1715.61  5372.7 1716.79  5402.8 1716.92
  5423.0 1718.25  5433.0 1717.58  5493.4 1718.73  5502.1 1720.21  5505.9 1720.21
#Mann=3,-1,0
  4416.2    0.05       0  4998.4    0.03       0  5002.7    0.05       0
Bank Sta=4998.4,5002.7
Exp/Cntr=0.3,0.1

Chan Stop Cuts=-1