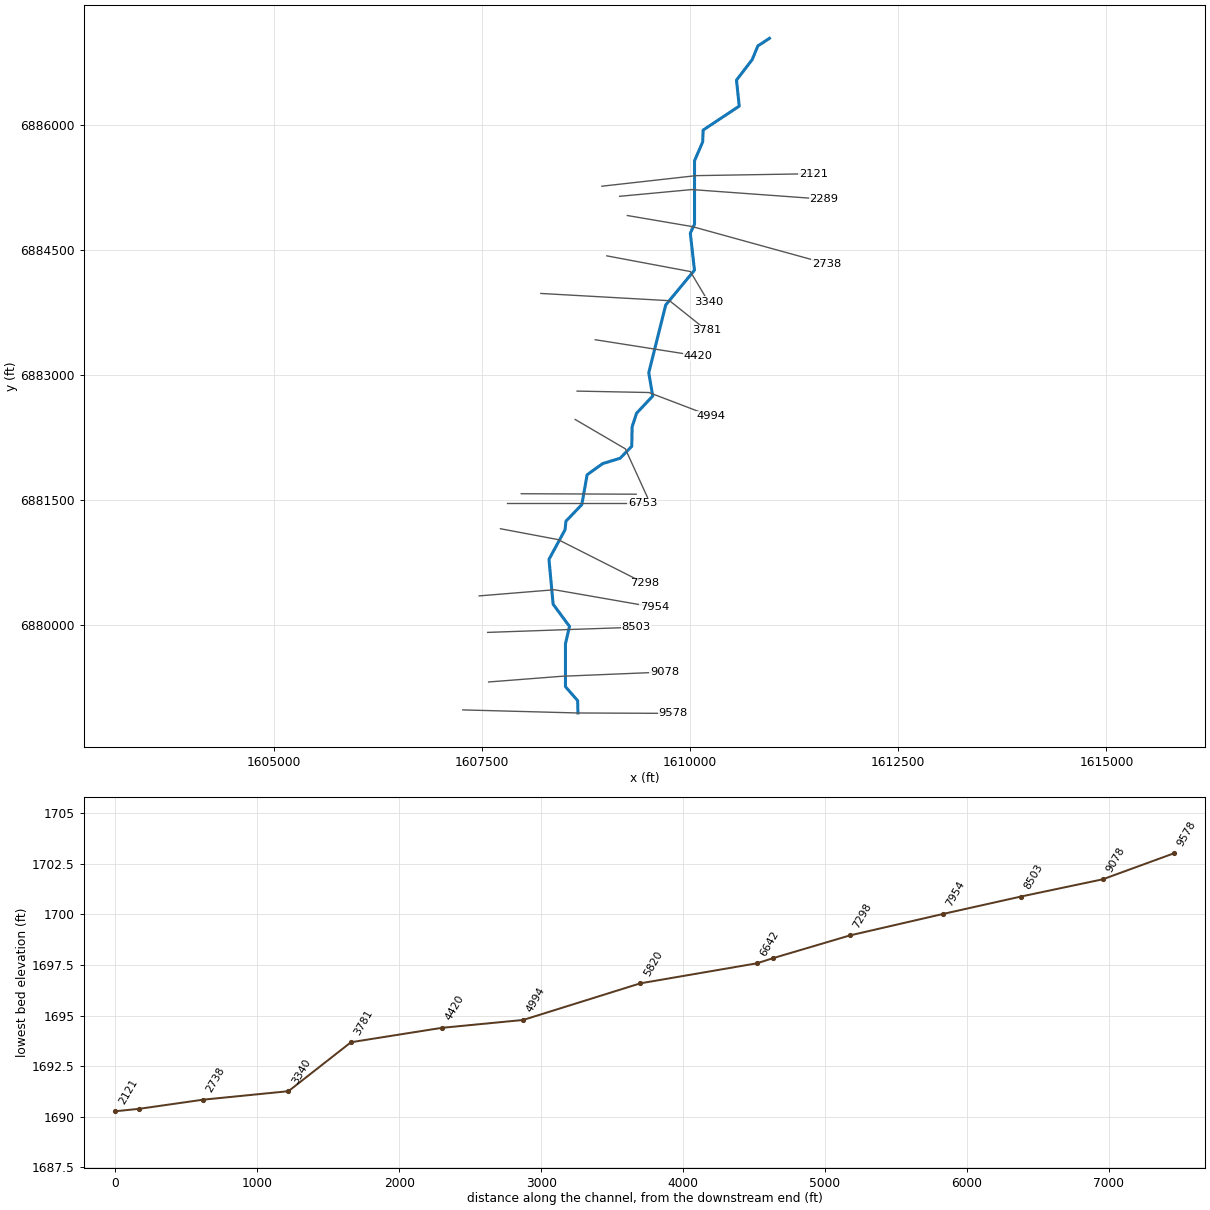
--- Deadman 56.prj (project) ---

Proj Title=Deadman 56 Base Level Engineering
Current Plan=p01
Default Exp/Contr=0.3,0.1
English Units
Geom File=g01
Flow File=f01
Plan File=p01
BEGIN DESCRIPTION:
Deadman 56
END DESCRIPTION:

--- Deadman 56.p01 (plan) ---

Plan Title=Multiple Run
Short Identifier=Multiple
Geom File=g01
Flow File=f01
Subcritical Flow
K Sum by GR= 0
Std Step Tol= 0.01
Critical Tol= 0.01
Num of Std Step Trials= 20
Max Error Tol= 0.3
Flow Tol Ratio= 0.001
Split Flow NTrial= 30
Split Flow Tol= 0.02
Split Flow Ratio= 0.02
Log Output Level= 0
Friction Slope Method= 1
Unsteady Friction Slope Method= 2
Unsteady Bridges Friction Slope Method= 1
Parabolic Critical Depth
Global Vel Dist=  1 , 1 , 1
Global Log Level= 0
CheckData=True
Encroach Param= -1, 0, 0, 0
BEGIN DESCRIPTION:
Multiple Run
END DESCRIPTION:

--- Deadman 56.f01 (steady flow) ---

Flow Title=Multiple
Number of Profiles=7
Profile Names=10-year,25-year,50-year,1pct_min,100-year,1pct_plu,500-year
River Rch & RM= Deadman 56,Reach-1,9578
     166     219     260     153     306     610     429
River Rch & RM= Deadman 56,Reach-1,9078
     258     349     422     254     506    1009     736
River Rch & RM= Deadman 56,Reach-1,2738
     289     394     478     288     575    1148     843
Boundary for River Rch & Prof#=Deadman 56,Reach-1,1
Up Type=0
Dn Type=3
Dn Slope=0.006
Boundary for River Rch & Prof#=Deadman 56,Reach-1,2
Up Type=0
Dn Type=3
Dn Slope=0.006
Boundary for River Rch & Prof#=Deadman 56,Reach-1,3
Up Type=0
Dn Type=3
Dn Slope=0.006
Boundary for River Rch & Prof#=Deadman 56,Reach-1,4
Up Type=0
Dn Type=3
Dn Slope=0.006
Boundary for River Rch & Prof#=Deadman 56,Reach-1,5
Up Type=0
Dn Type=3
Dn Slope=0.006
Boundary for River Rch & Prof#=Deadman 56,Reach-1,6
Up Type=0
Dn Type=3
Dn Slope=0.006
Boundary for River Rch & Prof#=Deadman 56,Reach-1,7
Up Type=0
Dn Type=3
Dn Slope=0.006

--- Deadman 56.g01 (geometry) ---

Geom Title=Existing Conditions

River Reach=Deadman 56,Reach-1
Reach XY= 30
      1608655.00      6878938.00      1608651.50      6879086.55
      1608505.38      6879253.16      1608505.07      6879767.97
      1608553.81      6879977.50      1608357.06      6880243.85
      1608307.26      6880782.06      1608501.17      6881139.59
      1608510.52      6881240.43      1608701.46      6881439.46
      1608765.39      6881798.10      1608952.58      6881932.46
      1609161.06      6881996.14      1609301.46      6882139.46
      1609305.52      6882372.78      1609358.81      6882536.44
      1609552.96      6882743.85      1609505.38      6883022.73
      1609708.82      6883836.42      1610054.09      6884253.94
      1610004.55      6884698.19      1610054.93      6884808.03
      1610055.07      6885567.97      1610152.73      6885793.94
      1610158.45      6885936.75      1610591.62      6886224.27
      1610558.55      6886536.53      1610746.84      6886781.95
      1610815.75      6886947.70      1610955.00      6887038.00

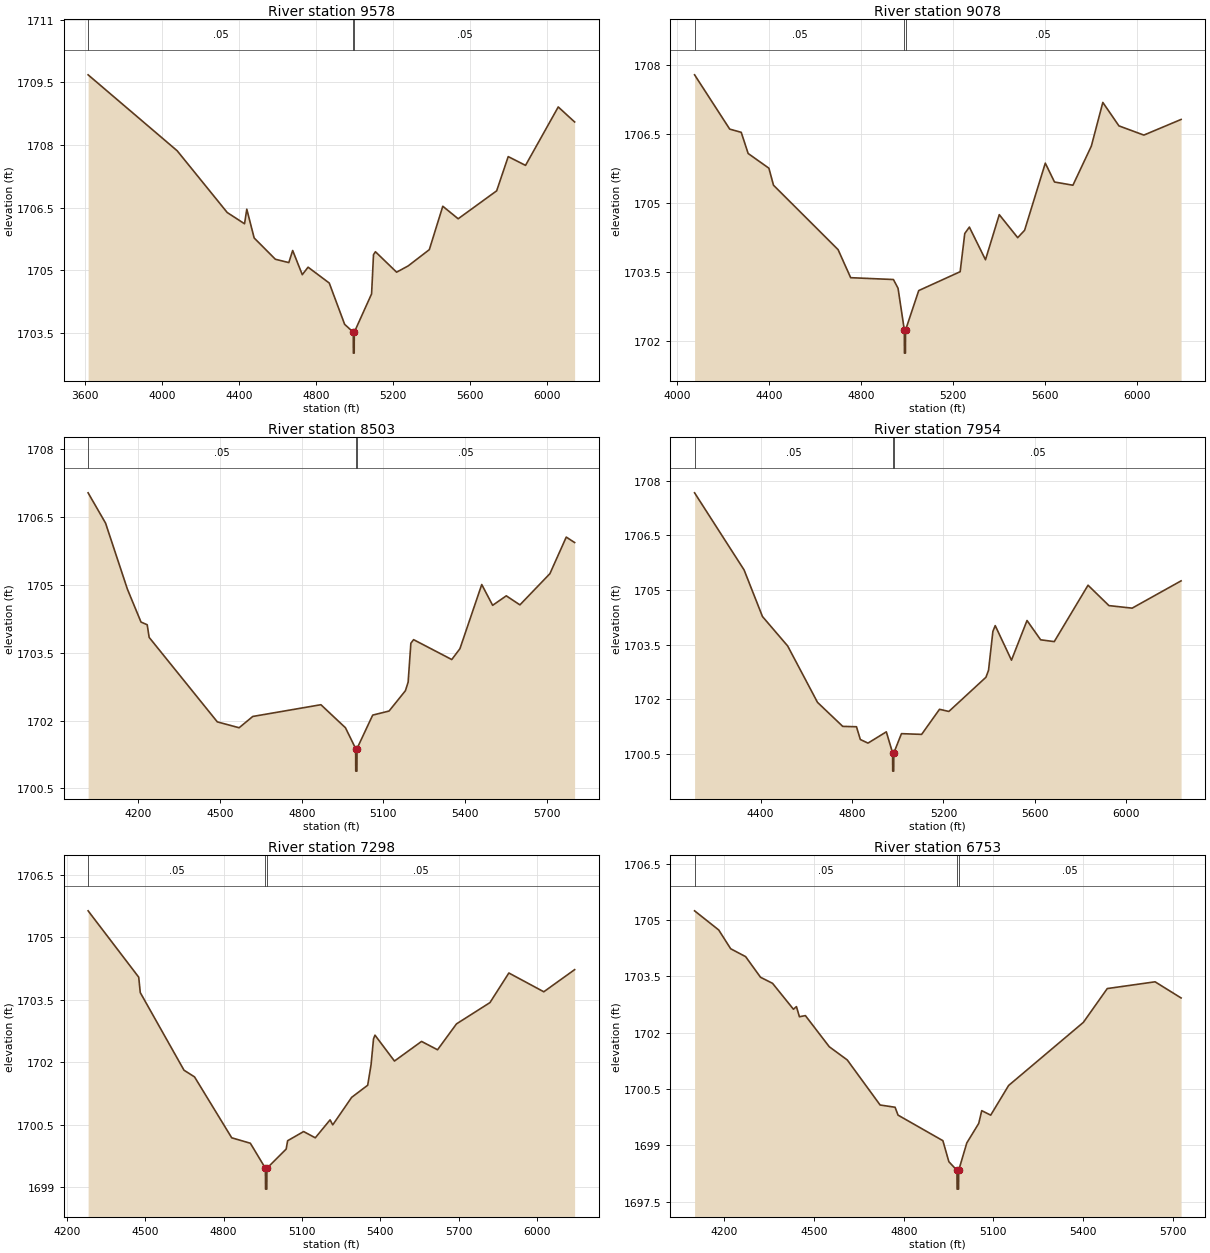
Type RM Length L Ch R = 1,9578,500,500,500
BEGIN DESCRIPTION:
Deadman 56 11.0
END DESCRIPTION:
XS GIS Cut Line= 3
      1607272.39      6878974.93      1608655.00      6878938.00
      1609800.09      6878933.26
#Sta/Elev= 30
  3616.9 1709.68  4079.7 1707.86  4339.8 1706.38  4429.8 1706.11  4441.5 1706.46
  4479.8 1705.77  4589.9 1705.26  4659.9 1705.18  4679.9 1705.47  4729.9 1704.89
  4759.9 1705.07  4870.0 1704.69  4950.0 1703.70  4995.0 1703.51  4995.3 1703.01
  4999.6 1703.01  5000.0 1703.51  5090.0 1704.43  5100.0 1705.37  5110.0 1705.44
  5220.0 1704.95  5280.0 1705.10  5390.0 1705.49  5460.0 1706.53  5540.0 1706.23
  5740.0 1706.90  5800.0 1707.72  5890.0 1707.51  6060.0 1708.91  6145.1 1708.55
#Mann=3,-1,0
  3616.9    0.05       0  4995.0    0.05       0  5000.0    0.05       0
Bank Sta=4995,5000
Exp/Cntr=0.3,0.1

Type RM Length L Ch R = 1,9078,575,575,575
BEGIN DESCRIPTION:
Mapping XS d3654cae
END DESCRIPTION:
XS GIS Cut Line= 3
      1607582.70      6879310.29      1608457.19      6879378.43
      1609695.09      6879429.54
#Sta/Elev= 30
  4074.7 1707.78  4227.5 1706.60  4277.6 1706.53  4307.7 1706.07  4398.0 1705.75
  4418.0 1705.38  4698.9 1703.98  4753.6 1703.37  4939.6 1703.33  4959.7 1703.14
  4987.1 1702.23  4987.5 1701.73  4991.8 1701.73  4992.2 1702.23  5049.7 1703.09
  5229.9 1703.50  5249.9 1704.33  5269.9 1704.47  5340.0 1703.76  5400.0 1704.74
  5480.1 1704.24  5510.1 1704.40  5600.2 1705.86  5640.2 1705.45  5720.3 1705.38
  5800.4 1706.23  5850.4 1707.18  5920.5 1706.67  6028.9 1706.47  6190.8 1706.81
#Mann=3,-1,0
  4074.7    0.05       0  4987.1    0.03       0  4992.2    0.05       0
Bank Sta=4987.1,4992.2
Exp/Cntr=0.3,0.1

Type RM Length L Ch R = 1,8503,549,549,549
BEGIN DESCRIPTION:
Mapping XS 007804c7
END DESCRIPTION:
XS GIS Cut Line= 2
      1607571.01      6879905.49      1609355.72      6879967.99
#Sta/Elev= 30
  4016.0 1707.04  4080.0 1706.37  4160.1 1704.91  4210.1 1704.18  4232.9 1704.12
  4240.1 1703.84  4490.3 1701.97  4570.3 1701.84  4620.4 1702.09  4870.5 1702.35
  4960.6 1701.84  4998.0 1701.38  4998.4 1700.88  5002.7 1700.88  5003.1 1701.38
  5060.6 1702.12  5120.7 1702.21  5180.7 1702.66  5190.7 1702.85  5200.7 1703.71
  5210.7 1703.79  5350.8 1703.35  5380.8 1703.59  5460.9 1705.01  5500.9 1704.55
  5550.9 1704.76  5601.0 1704.56  5711.0 1705.25  5771.1 1706.06  5801.8 1705.94
#Mann=3,-1,0
  4016.0    0.05       0  4998.0    0.03       0  5003.1    0.05       0
Bank Sta=4998,5003.1
Exp/Cntr=0.3,0.1

Type RM Length L Ch R = 1,7954,656,656,656
BEGIN DESCRIPTION:
Mapping XS 14a2f04c
END DESCRIPTION:
XS GIS Cut Line= 3
      1607469.11      6880343.80      1608372.01      6880417.62
      1609575.90      6880207.51
#Sta/Elev= 30
  4111.4 1707.67  4328.0 1705.55  4408.3 1704.27  4518.6 1703.46  4649.1 1701.91
  4759.4 1701.25  4819.6 1701.24  4836.3 1700.89  4869.8 1700.79  4950.1 1701.10
  4977.6 1700.52  4978.0 1700.02  4982.4 1700.02  4982.8 1700.52  5016.3 1701.05
  5104.5 1701.03  5182.8 1701.72  5223.6 1701.66  5385.8 1702.60  5397.1 1702.79
  5416.2 1703.86  5426.4 1704.02  5497.5 1703.07  5565.5 1704.16  5625.1 1703.63
  5684.6 1703.58  5832.4 1705.13  5923.8 1704.57  6025.3 1704.50  6239.4 1705.25
#Mann=3,-1,0
  4111.4    0.05       0  4977.6    0.03       0  4982.8    0.05       0
Bank Sta=4977.6,4982.8
Exp/Cntr=0.3,0.1

Type RM Length L Ch R = 1,7298,545,545,545
BEGIN DESCRIPTION:
Mapping XS d6f8892e
END DESCRIPTION:
XS GIS Cut Line= 3
      1607724.68      6881150.16      1608417.44      6881019.55
      1609450.50      6880497.35
#Sta/Elev= 30
  4281.6 1705.63  4475.3 1704.04  4481.3 1703.67  4648.7 1701.81  4689.0 1701.65
  4831.4 1700.19  4902.7 1700.06  4960.4 1699.46  4960.9 1698.96  4965.7 1698.96
  4966.1 1699.46  5039.8 1699.92  5045.4 1700.12  5106.7 1700.34  5151.3 1700.19
  5207.9 1700.62  5218.1 1700.50  5290.6 1701.16  5351.9 1701.45  5364.8 1701.94
  5374.2 1702.56  5379.8 1702.65  5454.4 1702.03  5558.1 1702.50  5619.3 1702.30
  5691.8 1702.92  5819.9 1703.43  5892.4 1704.14  6026.1 1703.69  6144.1 1704.22
#Mann=3,-1,0
  4281.6    0.05       0  4960.4    0.03       0  4966.1    0.05       0
Bank Sta=4960.4,4966.1
Exp/Cntr=0.3,0.1

Type RM Length L Ch R = 1,6753,111,111,111
BEGIN DESCRIPTION:
Mapping XS bc45f52c
END DESCRIPTION:
XS GIS Cut Line= 2
      1607804.19      6881456.81      1609431.99      6881456.81
#Sta/Elev= 30
  4100.3 1705.24  4181.1 1704.73  4221.1 1704.23  4271.1 1704.02  4321.1 1703.47
  4361.1 1703.31  4431.1 1702.62  4441.1 1702.69  4451.1 1702.42  4471.1 1702.45
  4551.1 1701.62  4611.1 1701.27  4721.1 1700.07  4771.1 1700.01  4781.1 1699.80
  4931.1 1699.12  4951.1 1698.56  4978.2 1698.33  4978.7 1697.83  4983.5 1697.83
  4984.0 1698.33  5011.1 1699.06  5051.1 1699.58  5061.1 1699.92  5091.1 1699.80
  5151.1 1700.59  5401.1 1702.27  5481.1 1703.17  5641.1 1703.35  5728.1 1702.92
#Mann=3,-1,0
  4100.3    0.05       0  4978.2    0.05       0  4984.0    0.05       0
Bank Sta=4978.2,4984
Exp/Cntr=0.3,0.1

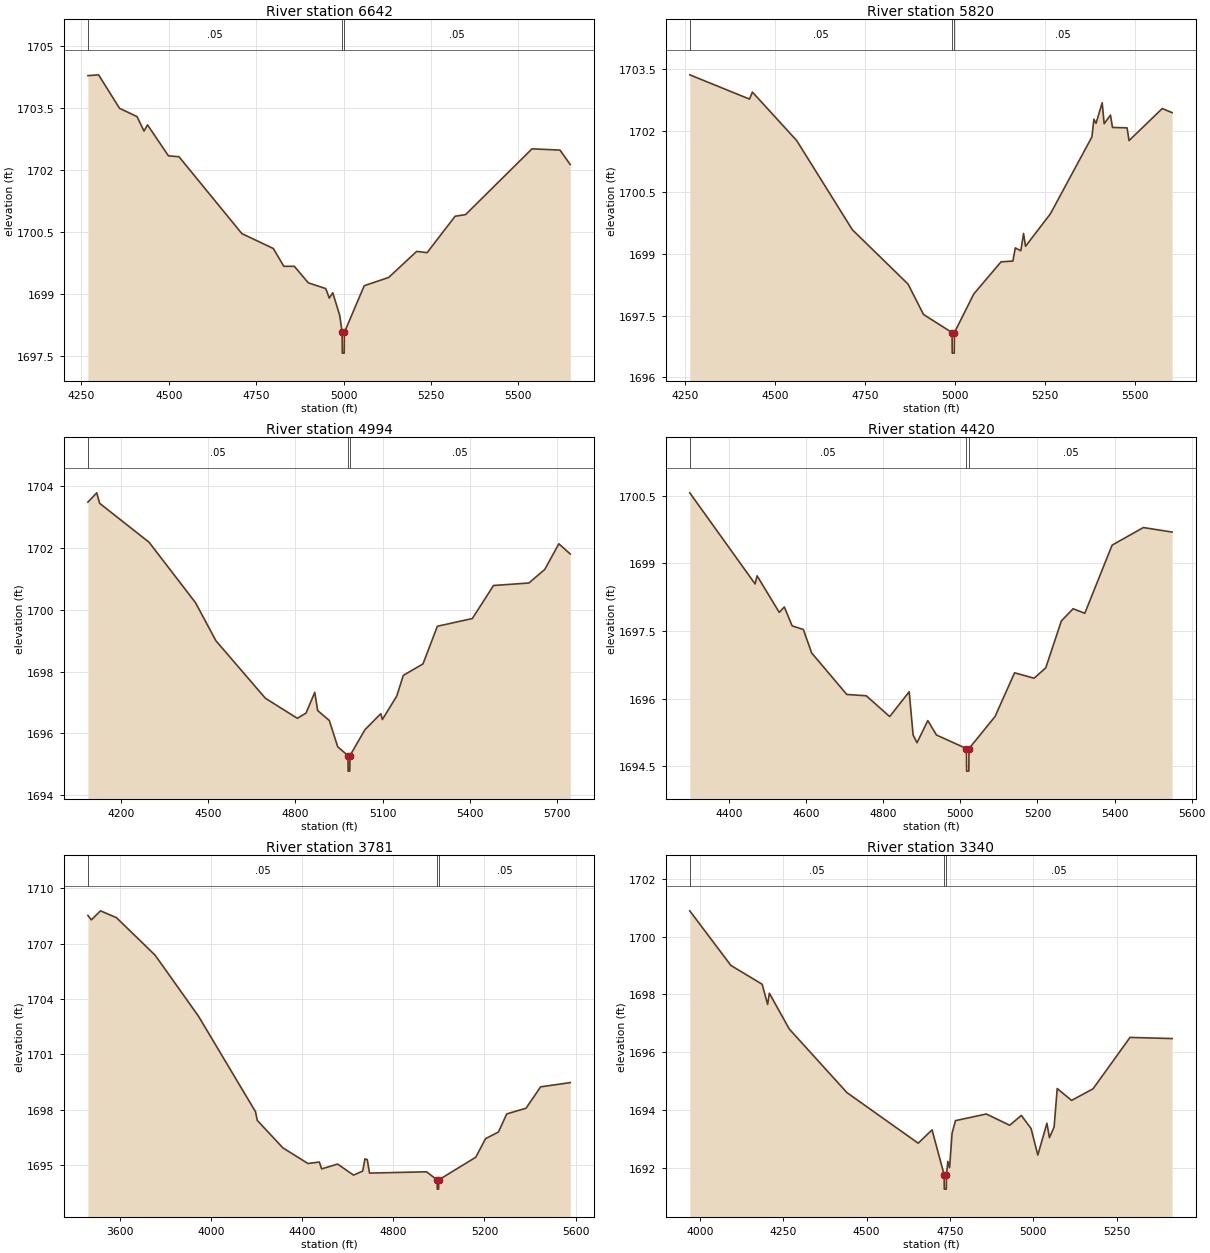
Type RM Length L Ch R = 1,6642,822,822,822
BEGIN DESCRIPTION:
Mapping XS ef45147c
END DESCRIPTION:
XS GIS Cut Line= 2
      1607974.53      6881570.38      1609354.42      6881564.70
#Sta/Elev= 30
  4268.6 1704.29  4299.1 1704.31  4359.1 1703.50  4409.1 1703.30  4429.1 1702.95
  4439.1 1703.10  4499.1 1702.35  4529.1 1702.33  4709.1 1700.47  4799.1 1700.11
  4829.1 1699.68  4859.1 1699.68  4899.1 1699.28  4949.1 1699.14  4959.1 1698.91
  4969.1 1699.04  4989.1 1698.49  4995.9 1698.08  4996.4 1697.58  5001.8 1697.58
  5002.3 1698.08  5059.1 1699.21  5129.1 1699.41  5209.1 1700.04  5239.1 1700.01
  5319.1 1700.89  5349.1 1700.93  5539.1 1702.52  5619.1 1702.49  5648.5 1702.14
#Mann=3,-1,0
  4268.6    0.05       0  4995.9    0.05       0  5002.3    0.05       0
Bank Sta=4995.9,5002.3
Exp/Cntr=0.3,0.1

Type RM Length L Ch R = 1,5820,826,826,826
BEGIN DESCRIPTION:
Mapping XS 3e607d72
END DESCRIPTION:
XS GIS Cut Line= 3
      1608621.84      6882461.94      1609223.80      6882109.85
      1609490.33      6881525.76
#Sta/Elev= 30
  4262.8 1703.36  4428.6 1702.77  4436.7 1702.94  4559.8 1701.76  4714.4 1699.59
  4868.9 1698.27  4911.9 1697.53  4991.1 1697.09  4991.6 1696.59  4997.2 1696.59
  4997.7 1697.09  5051.5 1698.03  5127.1 1698.81  5160.1 1698.83  5166.7 1699.15
  5182.0 1699.08  5189.7 1699.50  5195.2 1699.19  5264.3 1699.98  5379.5 1701.85
  5385.0 1702.28  5390.9 1702.18  5408.0 1702.68  5413.5 1702.17  5431.1 1702.38
  5436.6 1702.08  5477.1 1702.07  5482.6 1701.76  5574.8 1702.54  5602.2 1702.44
#Mann=3,-1,0
  4262.8    0.05       0  4991.1    0.05       0  4997.7    0.05       0
Bank Sta=4991.1,4997.7
Exp/Cntr=0.3,0.1

Type RM Length L Ch R = 1,4994,574,574,574
BEGIN DESCRIPTION:
Mapping XS fff9ddc9
END DESCRIPTION:
XS GIS Cut Line= 3
      1608644.56      6882802.64      1609507.74      6882785.60
      1610251.65      6882501.67
#Sta/Elev= 30
  4086.0 1703.49  4116.4 1703.79  4126.4 1703.45  4296.5 1702.19  4456.5 1700.23
  4526.5 1699.00  4696.6 1697.14  4806.6 1696.49  4836.6 1696.66  4866.6 1697.33
  4876.6 1696.74  4916.6 1696.42  4945.5 1695.57  4980.9 1695.28  4981.4 1694.78
  4987.1 1694.78  4987.6 1695.28  5039.1 1696.12  5093.9 1696.64  5099.2 1696.45
  5148.7 1697.21  5171.2 1697.88  5238.9 1698.25  5288.4 1699.47  5408.7 1699.72
  5481.6 1700.79  5603.2 1700.87  5658.0 1701.31  5706.4 1702.14  5745.6 1701.81
#Mann=3,-1,0
  4086.0    0.05       0  4980.9    0.05       0  4987.6    0.05       0
Bank Sta=4980.9,4987.6
Exp/Cntr=0.3,0.1

Type RM Length L Ch R = 1,4420,639,639,639
BEGIN DESCRIPTION:
Mapping XS 8dd988c0
END DESCRIPTION:
XS GIS Cut Line= 2
      1608862.67      6883419.37      1610098.77      6883224.93
#Sta/Elev= 30
  4298.0 1700.56  4467.5 1698.54  4472.6 1698.72  4530.1 1697.91  4543.3 1698.03
  4563.6 1697.61  4592.6 1697.53  4614.2 1697.01  4705.3 1696.09  4755.9 1696.06
  4816.6 1695.60  4867.2 1696.15  4877.4 1695.19  4887.5 1695.02  4915.5 1695.51
  4938.1 1695.19  5015.7 1694.89  5016.2 1694.39  5021.9 1694.39  5022.4 1694.89
  5089.9 1695.60  5140.6 1696.57  5191.2 1696.45  5221.5 1696.68  5262.0 1697.72
  5292.4 1697.99  5322.8 1697.89  5393.6 1699.40  5474.6 1699.79  5549.3 1699.69
#Mann=3,-1,0
  4298.0    0.05       0  5015.7    0.03       0  5022.4    0.05       0
Bank Sta=5015.7,5022.4
Exp/Cntr=0.3,0.1

Type RM Length L Ch R = 1,3781,441,441,441
BEGIN DESCRIPTION:
Deadman 56 3.0
END DESCRIPTION:
XS GIS Cut Line= 3
      1608209.86      6883974.93      1609755.00      6883888.00
      1610201.45      6883531.67
#Sta/Elev= 30
  3458.1 1708.53  3473.3 1708.29  3513.3 1708.78  3583.4 1708.41  3753.7 1706.37
  3944.0 1703.06  4194.4 1697.88  4202.0 1697.41  4314.6 1695.92  4424.8 1695.07
  4474.8 1695.15  4484.9 1694.78  4555.0 1695.04  4625.1 1694.44  4665.1 1694.66
  4675.2 1695.32  4685.2 1695.28  4695.2 1694.55  4945.6 1694.62  4992.3 1694.18
  4992.8 1693.68  4998.6 1693.68  4999.1 1694.18  5161.8 1695.41  5205.0 1696.42
  5261.6 1696.78  5297.9 1697.76  5382.8 1698.07  5446.8 1699.23  5576.9 1699.46
#Mann=3,-1,0
  3458.1    0.05       0  4992.3    0.05       0  4999.1    0.05       0
Bank Sta=4992.3,4999.1
Exp/Cntr=0.3,0.1

Type RM Length L Ch R = 1,3340,602,602,602
BEGIN DESCRIPTION:
Deadman 56 2.0
END DESCRIPTION:
XS GIS Cut Line= 3
      1609001.59      6884426.31      1610005.00      6884238.00
      1610223.10      6883871.87
#Sta/Elev= 30
  3969.4 1700.89  4092.8 1699.00  4186.5 1698.35  4203.0 1697.65  4208.1 1698.04
  4267.9 1696.80  4440.9 1694.60  4654.6 1692.85  4696.3 1693.31  4732.5 1691.76
  4733.0 1691.26  4739.0 1691.26  4739.5 1691.76  4743.7 1692.22  4748.8 1692.00
  4756.3 1693.19  4766.5 1693.63  4859.0 1693.86  4929.3 1693.47  4964.1 1693.81
  4993.2 1693.36  5013.6 1692.44  5040.9 1693.54  5048.5 1693.04  5062.4 1693.41
  5071.8 1694.74  5114.9 1694.33  5179.2 1694.73  5290.2 1696.51  5416.5 1696.47
#Mann=3,-1,0
  3969.4    0.05       0  4732.5    0.05       0  4739.5    0.05       0
Bank Sta=4732.5,4739.5
Exp/Cntr=0.3,0.1

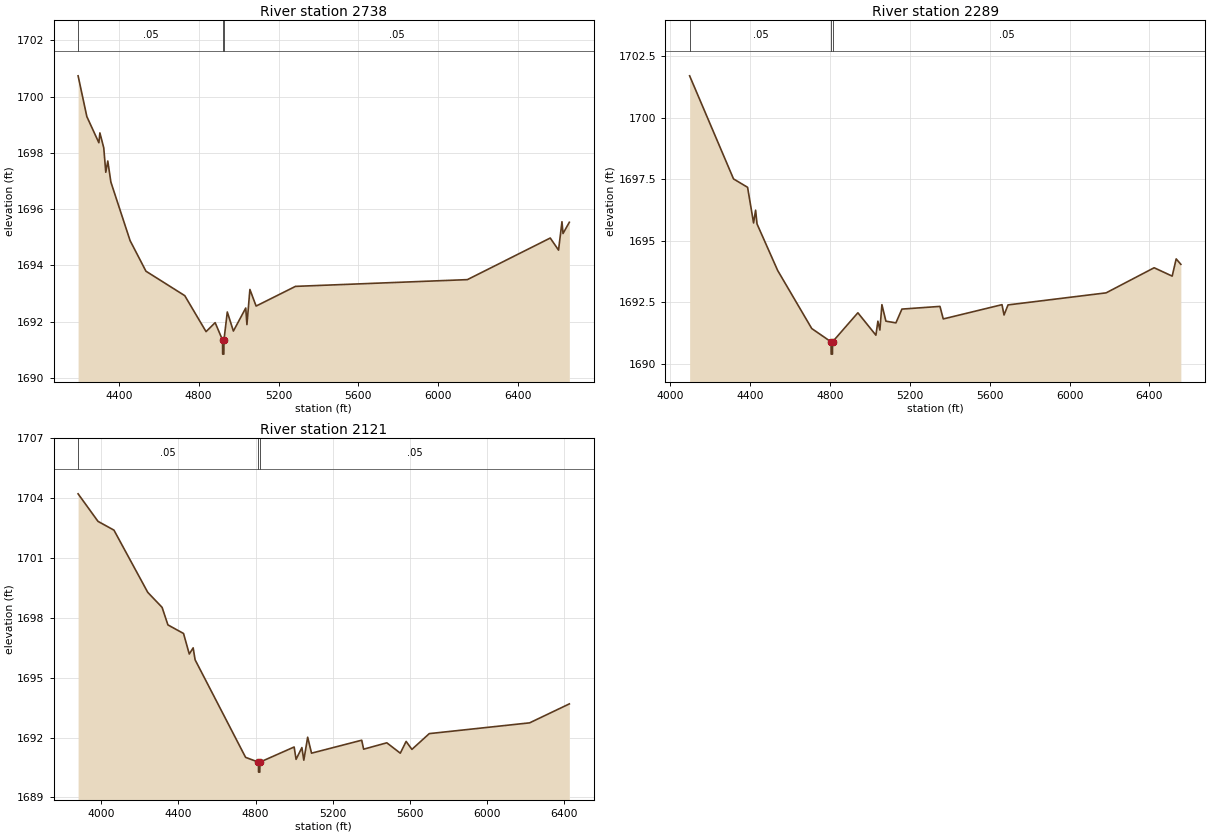
Type RM Length L Ch R = 1,2738,449,449,449
BEGIN DESCRIPTION:
Mapping XS 51ca0737
END DESCRIPTION:
XS GIS Cut Line= 3
      1609248.37      6884910.63      1610027.30      6884777.92
      1611637.06      6884333.65
#Sta/Elev= 30
  4196.2 1700.74  4240.0 1699.29  4300.2 1698.36  4305.3 1698.71  4324.7 1698.18
  4334.8 1697.31  4344.9 1697.71  4360.4 1696.96  4456.5 1694.88  4536.0 1693.79
  4730.4 1692.92  4837.0 1691.64  4882.6 1691.96  4919.6 1691.34  4920.1 1690.84
  4926.2 1690.84  4926.7 1691.34  4943.4 1692.34  4973.9 1691.66  5035.8 1692.48
  5041.7 1691.89  5056.6 1693.14  5087.7 1692.55  5284.8 1693.25  6145.8 1693.49
  6560.8 1694.97  6602.3 1694.54  6619.5 1695.55  6624.7 1695.13  6656.3 1695.53
#Mann=3,-1,0
  4196.2    0.05       0  4919.6    0.05       0  4926.7    0.05       0
Bank Sta=4919.6,4926.7
Exp/Cntr=0.3,0.1

Type RM Length L Ch R = 1,2289,168,168,168
BEGIN DESCRIPTION:
Mapping XS 9b0238c1
END DESCRIPTION:
XS GIS Cut Line= 3
      1609156.06      6885141.42      1610021.53      6885222.20
      1611608.30      6885106.80
#Sta/Elev= 30
  4097.2 1701.70  4317.1 1697.51  4387.4 1697.17  4417.5 1695.72  4427.6 1696.24
  4434.8 1695.68  4538.1 1693.79  4708.8 1691.43  4805.5 1690.89  4806.0 1690.39
  4812.5 1690.39  4813.0 1690.89  4939.8 1692.07  5030.1 1691.16  5040.1 1691.73
  5050.1 1691.37  5060.2 1692.40  5080.2 1691.73  5130.3 1691.66  5160.4 1692.22
  5350.9 1692.33  5367.5 1691.82  5661.7 1692.40  5671.8 1691.98  5691.8 1692.39
  6183.1 1692.88  6423.7 1693.90  6514.0 1693.56  6534.0 1694.26  6557.4 1694.04
#Mann=3,-1,0
  4097.2    0.05       0  4805.5    0.05       0  4813.0    0.05       0
Bank Sta=4805.5,4813
Exp/Cntr=0.3,0.1

Type RM Length L Ch R = 1,2121,0,0,0
BEGIN DESCRIPTION:
Deadman 56 1.0
END DESCRIPTION:
XS GIS Cut Line= 3
      1608942.52      6885262.59      1610073.46      6885389.53
      1611480.63      6885412.60
#Sta/Elev= 30
  3880.5 1704.22  3983.6 1702.84  4066.3 1702.40  4241.5 1699.28  4315.7 1698.53
  4345.9 1697.65  4426.8 1697.22  4456.6 1696.19  4476.7 1696.50  4486.8 1695.90
  4748.4 1691.01  4815.1 1690.77  4815.6 1690.27  4822.1 1690.27  4822.6 1690.77
  5000.0 1691.53  5010.0 1690.91  5040.1 1691.50  5050.1 1690.87  5070.1 1692.02
  5090.1 1691.22  5350.1 1691.87  5360.1 1691.42  5480.1 1691.74  5550.1 1691.22
  5580.2 1691.81  5610.2 1691.41  5700.2 1692.20  6220.2 1692.74  6425.9 1693.69
#Mann=3,-1,0
  3880.5    0.05       0  4815.1    0.05       0  4822.6    0.05       0
Bank Sta=4815.1,4822.6
Exp/Cntr=0.3,0.1

Chan Stop Cuts=-1