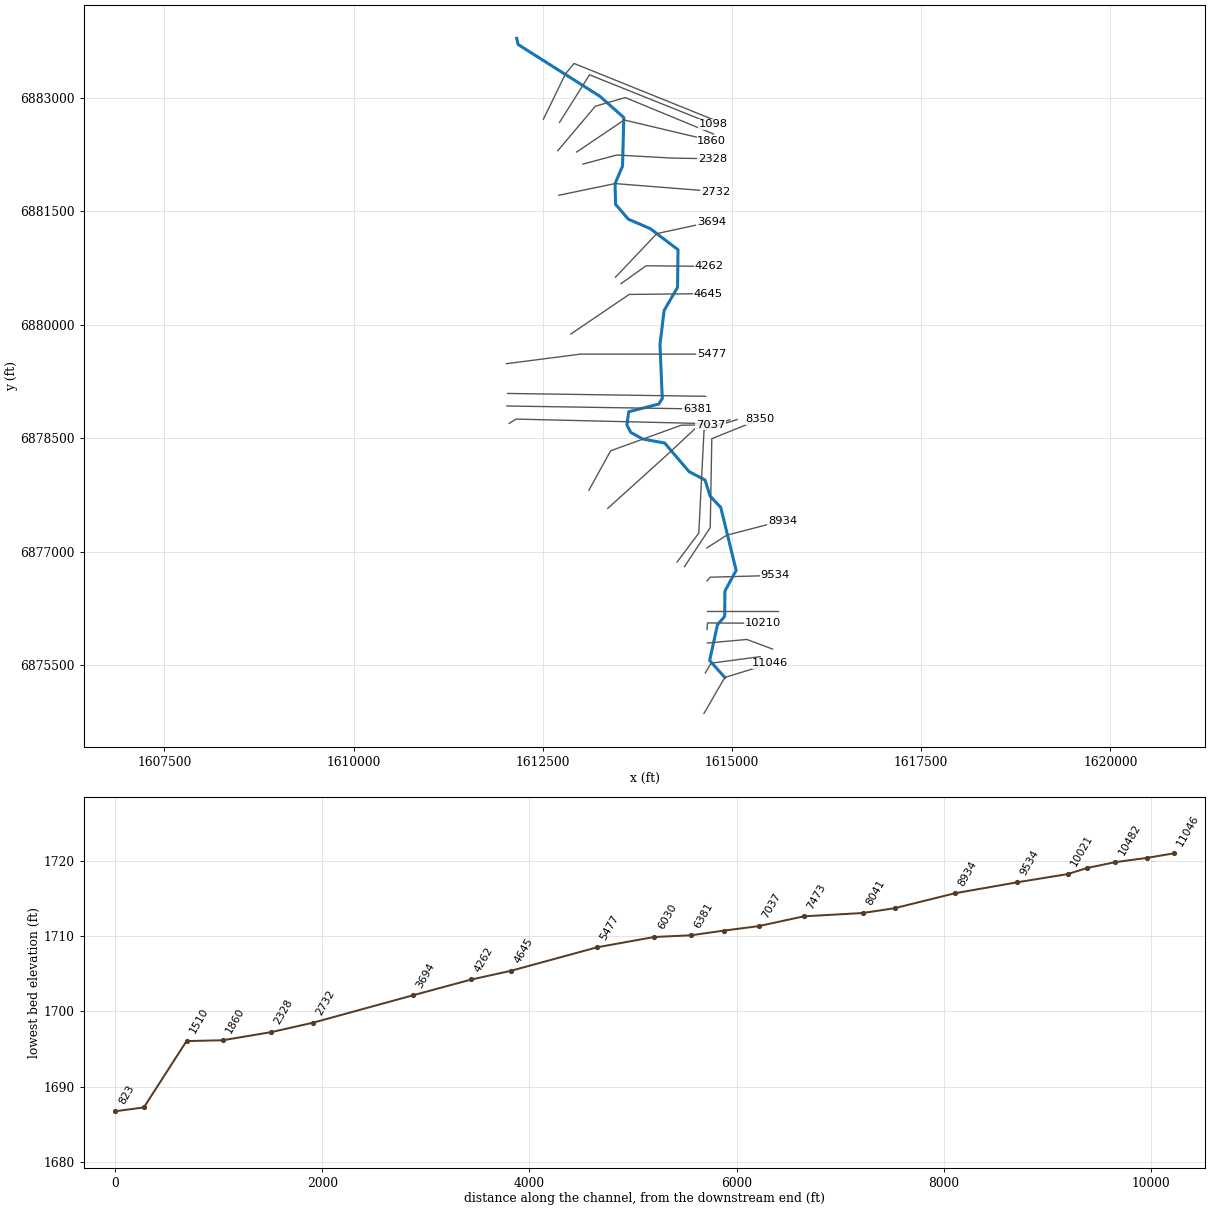
--- Deadman 57.prj (project) ---

Proj Title=Deadman 57 Base Level Engineering
Current Plan=p01
Default Exp/Contr=0.3,0.1
English Units
Geom File=g01
Flow File=f01
Plan File=p01
BEGIN DESCRIPTION:
Deadman 57
END DESCRIPTION:

--- Deadman 57.p01 (plan) ---

Plan Title=Multiple Run
Short Identifier=Multiple
Geom File=g01
Flow File=f01
Subcritical Flow
K Sum by GR= 0
Std Step Tol= 0.01
Critical Tol= 0.01
Num of Std Step Trials= 20
Max Error Tol= 0.3
Flow Tol Ratio= 0.001
Split Flow NTrial= 30
Split Flow Tol= 0.02
Split Flow Ratio= 0.02
Log Output Level= 0
Friction Slope Method= 1
Unsteady Friction Slope Method= 2
Unsteady Bridges Friction Slope Method= 1
Parabolic Critical Depth
Global Vel Dist=  1 , 1 , 1
Global Log Level= 0
CheckData=True
Encroach Param= -1, 0, 0, 0
BEGIN DESCRIPTION:
Multiple Run
END DESCRIPTION:

--- Deadman 57.f01 (steady flow) ---

Flow Title=Multiple
Number of Profiles=7
Profile Names=10-year,25-year,50-year,1pct_min,100-year,1pct_plu,500-year
River Rch & RM= Deadman 57,Reach-1,11046
     132     172     203     119     237     473     329
River Rch & RM= Deadman 57,Reach-1,10021
     191     254     304     181     361     721     515
River Rch & RM= Deadman 57,Reach-1,6381
     282     382     462     278     554    1106     807
River Rch & RM= Deadman 57,Reach-1,1098
    2859    4320    5630    3628    7238   14442   12127
Boundary for River Rch & Prof#=Deadman 57,Reach-1,1
Up Type=0
Dn Type=3
Dn Slope=0.05
Boundary for River Rch & Prof#=Deadman 57,Reach-1,2
Up Type=0
Dn Type=3
Dn Slope=0.05
Boundary for River Rch & Prof#=Deadman 57,Reach-1,3
Up Type=0
Dn Type=3
Dn Slope=0.05
Boundary for River Rch & Prof#=Deadman 57,Reach-1,4
Up Type=0
Dn Type=3
Dn Slope=0.05
Boundary for River Rch & Prof#=Deadman 57,Reach-1,5
Up Type=0
Dn Type=3
Dn Slope=0.05
Boundary for River Rch & Prof#=Deadman 57,Reach-1,6
Up Type=0
Dn Type=3
Dn Slope=0.05
Boundary for River Rch & Prof#=Deadman 57,Reach-1,7
Up Type=0
Dn Type=3
Dn Slope=0.05

--- Deadman 57.g01 (geometry) ---

Geom Title=Existing Conditions

River Reach=Deadman 57,Reach-1
Reach XY= 30
      1614905.00      6875338.00      1614704.68      6875562.89
      1614808.55      6876036.53      1614902.93      6876143.86
      1614907.24      6876482.07      1615054.92      6876753.39
      1614851.46      6877586.53      1614710.83      6877735.70
      1614644.49      6877947.81      1614431.48      6878060.88
      1614111.01      6878437.22      1613818.32      6878490.94
      1613663.09      6878577.80      1613611.35      6878675.73
      1613635.37      6878851.29      1614032.67      6878952.92
      1614078.87      6879026.84      1614048.59      6879739.43
      1614103.10      6880189.18      1614280.28      6880495.82
      1614287.09      6880993.27      1613919.12      6881272.66
      1613629.83      6881397.70      1613461.67      6881593.58
      1613455.07      6881867.97      1613553.78      6882098.50
      1613570.70      6882741.13      1613254.74      6883022.29
      1612174.91      6883706.33      1612155.00      6883788.48

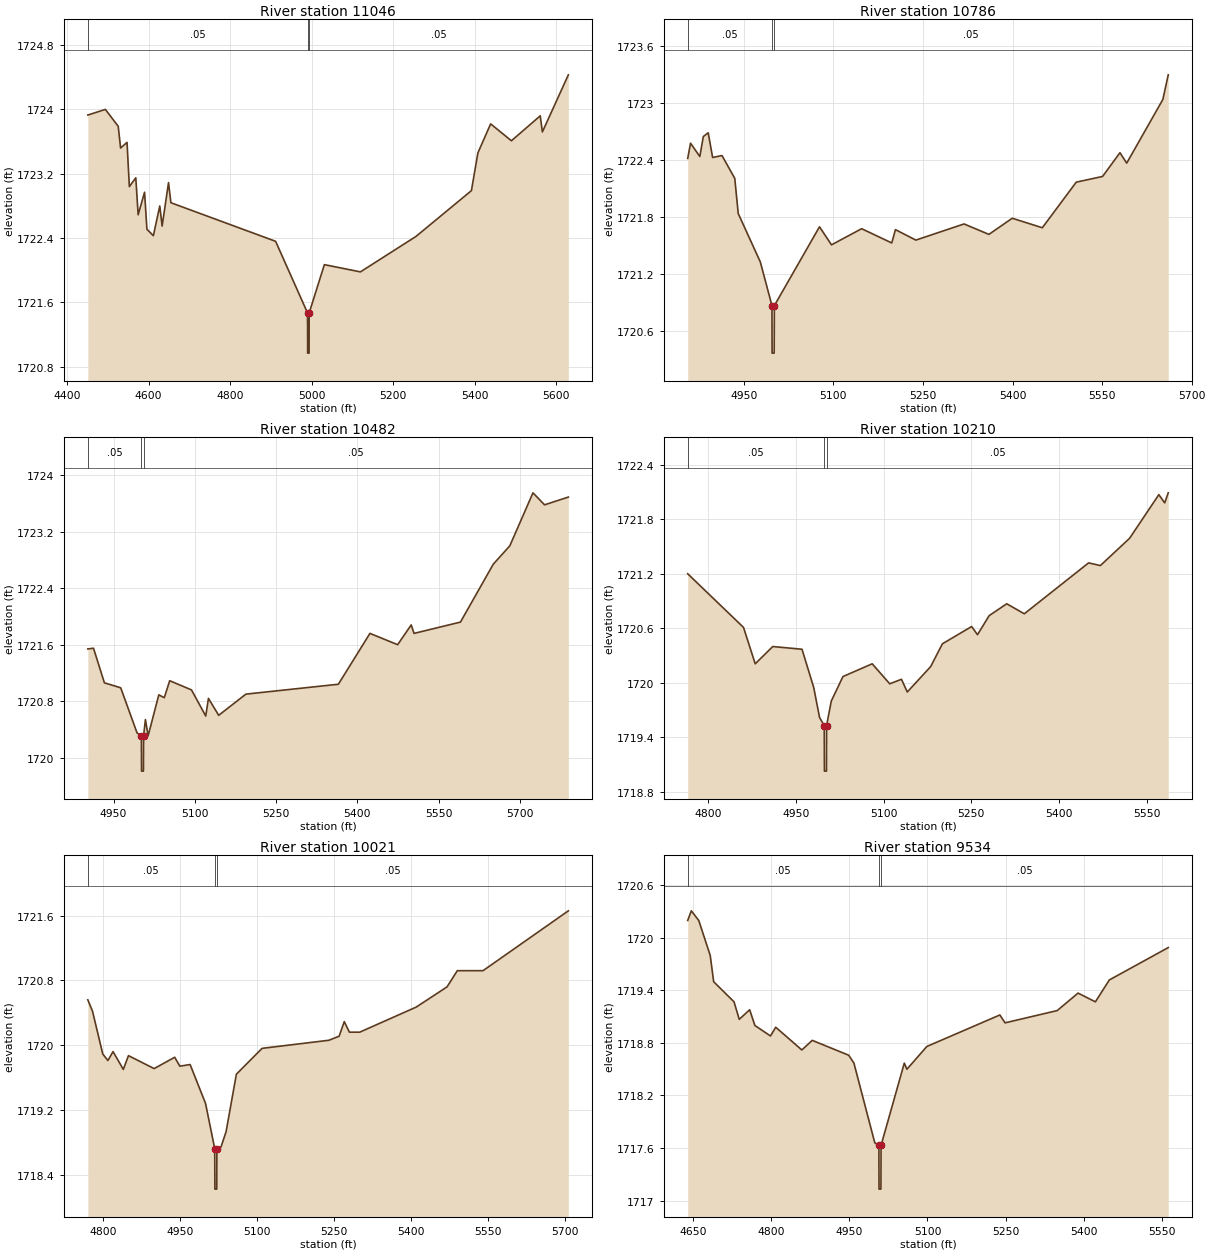
Type RM Length L Ch R = 1,11046,260,260,260
BEGIN DESCRIPTION:
Deadman 57 6.0
END DESCRIPTION:
XS GIS Cut Line= 3
      1614629.98      6874862.97      1614905.00      6875338.00
      1615507.16      6875522.86
#Sta/Elev= 30
  4451.1 1723.93  4494.2 1724.00  4525.7 1723.79  4531.5 1723.52  4547.3 1723.59
  4553.0 1723.04  4568.8 1723.15  4574.6 1722.69  4590.3 1722.97  4596.1 1722.51
  4611.9 1722.43  4627.6 1722.80  4633.4 1722.55  4649.1 1723.09  4654.9 1722.84
  4911.8 1722.36  4990.1 1721.47  4990.4 1720.97  4993.9 1720.97  4994.1 1721.47
  5031.4 1722.07  5119.8 1721.98  5255.9 1722.42  5392.1 1722.99  5408.0 1723.46
  5439.3 1723.82  5490.2 1723.61  5560.9 1723.92  5566.2 1723.72  5629.9 1724.43
#Mann=3,-1,0
  4451.1    0.05       0  4990.1   0.035       0  4994.1    0.05       0
Bank Sta=4990.1,4994.1
Exp/Cntr=0.3,0.1

Type RM Length L Ch R = 1,10786,304,304,304
BEGIN DESCRIPTION:
Mapping XS 6e1d5c98
END DESCRIPTION:
XS GIS Cut Line= 3
      1614647.85      6875398.51      1614723.87      6875526.56
      1615374.01      6875613.19
#Sta/Elev= 30
  4856.0 1722.42  4860.7 1722.58  4876.3 1722.44  4882.1 1722.65  4890.3 1722.69
  4897.7 1722.43  4913.4 1722.45  4934.8 1722.21  4940.6 1721.84  4977.6 1721.33
  4997.1 1720.87  4997.3 1720.37  5000.8 1720.37  5001.1 1720.87  5076.7 1721.70
  5096.8 1721.51  5147.3 1721.68  5197.7 1721.53  5203.9 1721.67  5238.1 1721.56
  5318.8 1721.73  5360.4 1721.62  5399.5 1721.79  5449.9 1721.69  5506.7 1722.17
  5550.8 1722.23  5579.9 1722.48  5591.2 1722.37  5651.7 1723.04  5660.8 1723.30
#Mann=3,-1,0
  4856.0    0.05       0  4997.1   0.035       0  5001.1    0.05       0
Bank Sta=4997.1,5001.1
Exp/Cntr=0.3,0.1

Type RM Length L Ch R = 1,10482,272,272,272
BEGIN DESCRIPTION:
Mapping XS d7202f19
END DESCRIPTION:
XS GIS Cut Line= 3
      1614674.50      6875793.48      1615196.13      6875840.19
      1615536.17      6875713.19
#Sta/Elev= 30
  4902.6 1721.54  4913.1 1721.55  4933.2 1721.06  4963.3 1720.99  4993.5 1720.35
  5001.5 1720.31  5001.7 1719.81  5005.2 1719.81  5005.5 1720.31  5008.9 1720.54
  5013.9 1720.31  5033.6 1720.89  5043.7 1720.85  5053.7 1721.09  5093.9 1720.96
  5120.2 1720.59  5125.2 1720.84  5144.1 1720.60  5194.3 1720.90  5364.9 1721.04
  5423.2 1721.76  5474.3 1721.60  5499.3 1721.88  5504.6 1721.76  5590.2 1721.92
  5650.8 1722.74  5681.3 1723.00  5724.0 1723.75  5745.4 1723.58  5789.3 1723.69
#Mann=3,-1,0
  4902.6    0.05       0  5001.5   0.035       0  5005.5    0.05       0
Bank Sta=5001.5,5005.5
Exp/Cntr=0.3,0.1

Type RM Length L Ch R = 1,10210,189,189,189
BEGIN DESCRIPTION:
Mapping XS ef4980a7
END DESCRIPTION:
XS GIS Cut Line= 3
      1614669.97      6875971.88      1614676.47      6876058.54
      1615411.06      6876054.71
#Sta/Elev= 30
  4765.2 1721.20  4860.6 1720.61  4880.6 1720.21  4910.6 1720.40  4960.6 1720.37
  4980.6 1719.95  4990.6 1719.62  4998.6 1719.53  4998.9 1719.03  5002.4 1719.03
  5002.6 1719.53  5010.6 1719.80  5030.6 1720.07  5080.6 1720.21  5110.6 1719.99
  5130.6 1720.04  5140.6 1719.90  5180.6 1720.18  5200.6 1720.43  5250.6 1720.62
  5260.6 1720.53  5280.6 1720.74  5310.6 1720.87  5340.6 1720.76  5450.6 1721.32
  5470.6 1721.29  5520.6 1721.59  5570.6 1722.07  5580.6 1721.98  5586.7 1722.09
#Mann=3,-1,0
  4765.2    0.05       0  4998.6   0.035       0  5002.6    0.05       0
Bank Sta=4998.6,5002.6
Exp/Cntr=0.3,0.1

Type RM Length L Ch R = 1,10021,487,487,487
BEGIN DESCRIPTION:
Mapping XS 51eabf91
END DESCRIPTION:
XS GIS Cut Line= 2
      1614675.85      6876214.76      1615611.05      6876214.76
#Sta/Elev= 30
  4770.5 1720.56  4779.6 1720.42  4799.6 1719.89  4809.6 1719.81  4819.6 1719.92
  4839.6 1719.70  4849.6 1719.87  4899.6 1719.71  4939.6 1719.85  4949.6 1719.74
  4969.6 1719.76  4999.6 1719.28  5017.5 1718.72  5017.8 1718.22  5021.4 1718.22
  5021.7 1718.72  5029.6 1718.74  5039.6 1718.93  5059.6 1719.64  5109.6 1719.96
  5239.6 1720.06  5259.6 1720.11  5269.6 1720.29  5279.6 1720.16  5299.6 1720.16
  5409.6 1720.47  5469.6 1720.72  5489.6 1720.92  5539.6 1720.92  5705.7 1721.66
#Mann=3,-1,0
  4770.5    0.05       0  5017.5   0.035       0  5021.7    0.05       0
Bank Sta=5017.5,5021.7
Exp/Cntr=0.3,0.1

Type RM Length L Ch R = 1,9534,600,600,600
BEGIN DESCRIPTION:
Mapping XS addc16b9
END DESCRIPTION:
XS GIS Cut Line= 3
      1614669.17      6876613.44      1614711.57      6876663.32
      1615568.08      6876686.89
#Sta/Elev= 30
  4639.8 1720.20  4646.7 1720.31  4661.0 1720.20  4683.0 1719.80  4689.6 1719.50
  4728.7 1719.27  4738.7 1719.07  4758.7 1719.18  4768.7 1719.00  4798.7 1718.88
  4808.7 1718.98  4858.8 1718.72  4878.8 1718.83  4948.8 1718.66  4958.8 1718.57
  4998.8 1717.66  5006.7 1717.63  5007.0 1717.13  5010.6 1717.13  5010.9 1717.63
  5055.5 1718.57  5060.5 1718.50  5098.8 1718.76  5238.9 1719.12  5248.9 1719.03
  5348.9 1719.17  5389.0 1719.37  5422.3 1719.27  5449.0 1719.52  5562.1 1719.89
#Mann=3,-1,0
  4639.8    0.05       0  5006.7   0.035       0  5010.9    0.05       0
Bank Sta=5006.7,5010.9
Exp/Cntr=0.3,0.1

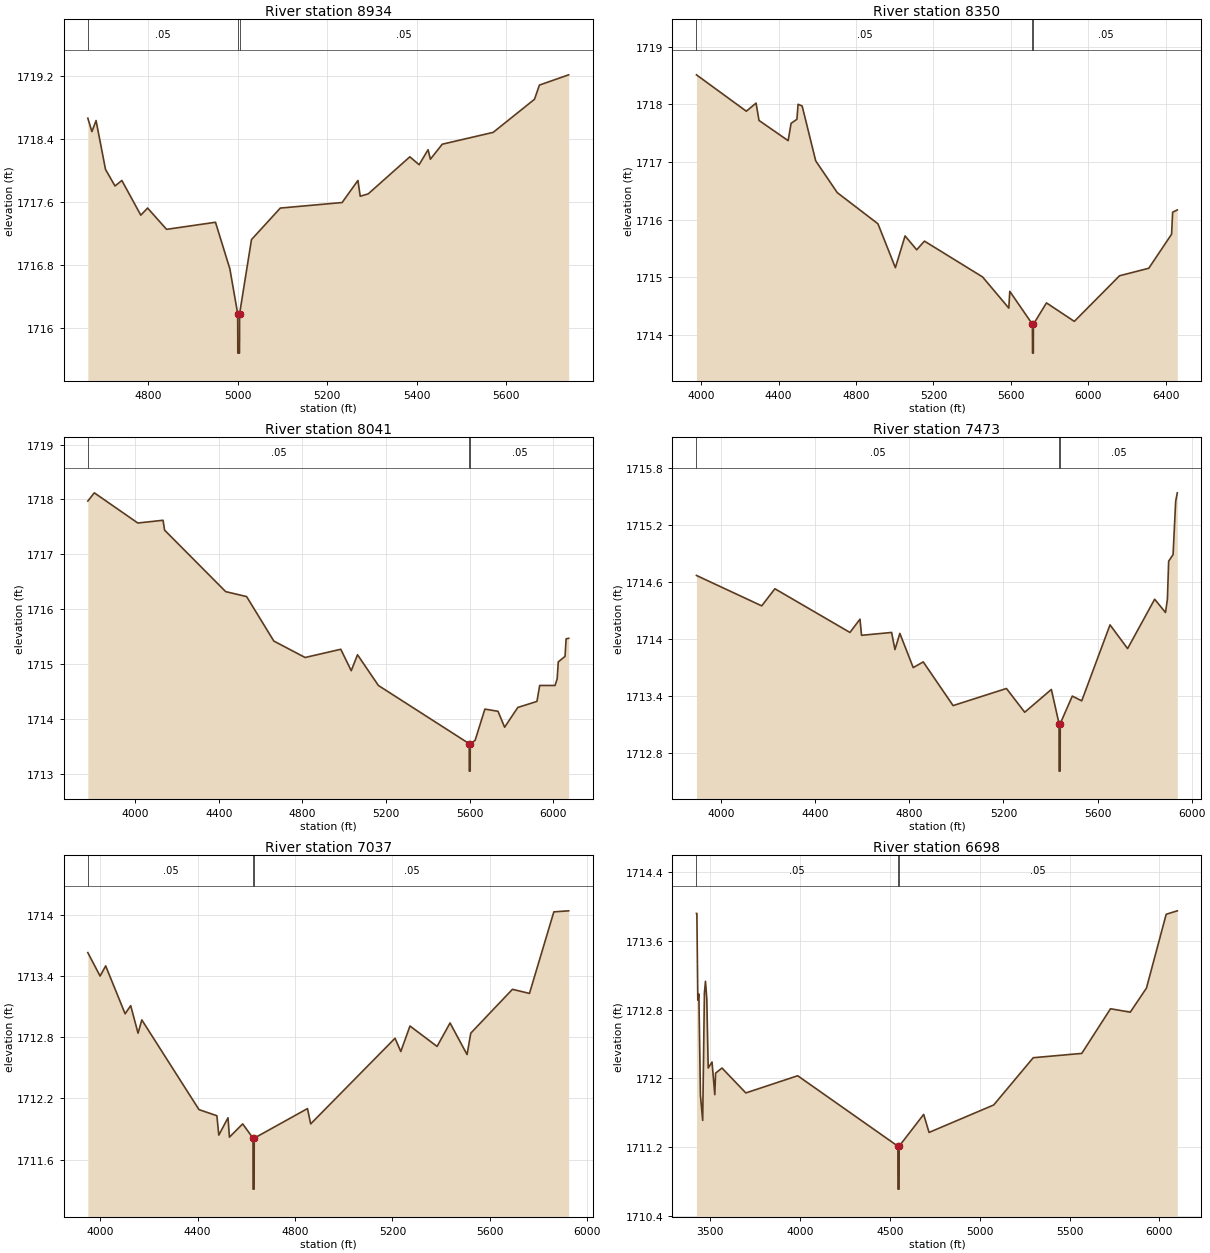
Type RM Length L Ch R = 1,8934,584,584,584
BEGIN DESCRIPTION:
Mapping XS dc5d0c8c
END DESCRIPTION:
XS GIS Cut Line= 3
      1614667.85      6877050.99      1614931.93      6877219.05
      1615668.17      6877411.11
#Sta/Elev= 30
  4665.3 1718.66  4674.4 1718.49  4683.7 1718.63  4704.8 1718.01  4726.0 1717.80
  4741.3 1717.87  4783.6 1717.43  4798.8 1717.52  4841.2 1717.25  4950.4 1717.34
  4982.5 1716.75  5000.0 1716.18  5000.3 1715.68  5004.0 1715.68  5004.3 1716.18
  5030.8 1717.12  5095.2 1717.52  5233.2 1717.59  5268.5 1717.87  5273.7 1717.67
  5291.5 1717.70  5384.5 1718.17  5405.2 1718.07  5425.2 1718.26  5430.4 1718.14
  5456.9 1718.33  5570.6 1718.48  5662.9 1718.90  5673.9 1719.08  5739.2 1719.21
#Mann=3,-1,0
  4665.3    0.05       0  5000.0   0.035       0  5004.3    0.05       0
Bank Sta=5000,5004.3
Exp/Cntr=0.3,0.1

Type RM Length L Ch R = 1,8350,309,309,309
BEGIN DESCRIPTION:
Mapping XS 1c4cccc4
END DESCRIPTION:
XS GIS Cut Line= 4
      1614372.62      6876803.03      1614712.67      6877319.24
      1614733.16      6878495.11      1615371.49      6878752.31
#Sta/Elev= 30
  3976.3 1718.51  4233.7 1717.88  4284.1 1718.02  4299.2 1717.72  4449.7 1717.37
  4464.8 1717.67  4494.9 1717.74  4500.9 1718.00  4522.0 1717.97  4592.0 1717.02
  4703.2 1716.47  4913.3 1715.93  5003.3 1715.17  5053.3 1715.72  5113.3 1715.48
  5153.3 1715.63  5453.3 1715.01  5588.9 1714.47  5593.9 1714.76  5710.9 1714.19
  5711.3 1713.69  5715.5 1713.69  5715.9 1714.19  5783.3 1714.56  5927.1 1714.24
  6160.6 1715.03  6311.5 1715.16  6429.3 1715.75  6434.7 1716.13  6458.7 1716.17
#Mann=3,-1,0
  3976.3    0.05       0  5710.9   0.035       0  5715.9    0.05       0
Bank Sta=5710.9,5715.9
Exp/Cntr=0.3,0.1

Type RM Length L Ch R = 1,8041,568,568,568
BEGIN DESCRIPTION:
Mapping XS 31d5c680
END DESCRIPTION:
XS GIS Cut Line= 4
      1614274.26      6876864.44      1614561.08      6877245.50
      1614630.73      6878609.83      1615067.22      6878748.07
#Sta/Elev= 30
  3773.6 1717.97  3804.6 1718.12  4012.8 1717.57  4133.6 1717.62  4141.0 1717.44
  4433.3 1716.32  4533.4 1716.23  4663.6 1715.42  4813.3 1715.12  4984.0 1715.27
  5034.1 1714.88  5064.1 1715.17  5164.2 1714.61  5598.6 1713.55  5599.0 1713.05
  5603.2 1713.05  5603.6 1713.55  5626.8 1713.61  5673.6 1714.18  5736.5 1714.14
  5768.0 1713.85  5831.0 1714.21  5922.7 1714.32  5935.8 1714.61  6009.2 1714.61
  6019.5 1714.73  6024.8 1715.04  6057.1 1715.14  6062.3 1715.46  6074.5 1715.47
#Mann=3,-1,0
  3773.6    0.05       0  5598.6   0.035       0  5603.6    0.05       0
Bank Sta=5598.6,5603.6
Exp/Cntr=0.3,0.1

Type RM Length L Ch R = 1,7473,436,436,436
BEGIN DESCRIPTION:
Mapping XS 63c52314
END DESCRIPTION:
XS GIS Cut Line= 5
      1613358.21      6877573.30      1614169.87      6878306.83
      1614517.09      6878632.35      1614712.40      6878645.37
      1614971.65      6878747.40
#Sta/Elev= 30
  3894.7 1714.67  4172.1 1714.35  4228.2 1714.53  4547.3 1714.07  4589.9 1714.21
  4596.6 1714.04  4724.4 1714.07  4738.6 1713.89  4759.5 1714.06  4816.3 1713.70
  4858.9 1713.76  4985.8 1713.30  5212.6 1713.48  5290.3 1713.23  5403.6 1713.47
  5436.3 1713.11  5436.6 1712.61  5440.9 1712.61  5441.3 1713.11  5492.6 1713.40
  5532.7 1713.35  5653.0 1714.15  5727.7 1713.90  5842.8 1714.42  5888.9 1714.28
  5897.0 1714.42  5902.3 1714.82  5921.1 1714.89  5932.1 1715.45  5939.0 1715.54
#Mann=3,-1,0
  3894.7    0.05       0  5436.3   0.035       0  5441.3    0.05       0
Bank Sta=5436.3,5441.3
Exp/Cntr=0.3,0.1

Type RM Length L Ch R = 1,7037,339,339,339
BEGIN DESCRIPTION:
Mapping XS 30cb4dd2
END DESCRIPTION:
XS GIS Cut Line= 4
      1613109.86      6877813.87      1613396.34      6878334.74
      1614329.50      6878673.28      1614715.75      6878677.62
#Sta/Elev= 30
  3949.9 1713.63  4000.3 1713.40  4023.1 1713.50  4103.0 1713.03  4125.8 1713.11
  4156.0 1712.84  4171.5 1712.97  4406.1 1712.09  4479.6 1712.03  4487.5 1711.84
  4525.2 1712.01  4531.1 1711.82  4585.5 1711.95  4627.8 1711.81  4628.1 1711.31
  4632.4 1711.31  4632.8 1711.81  4851.4 1712.10  4864.6 1711.95  5210.7 1712.79
  5234.4 1712.66  5272.0 1712.91  5383.3 1712.71  5436.5 1712.94  5506.3 1712.63
  5521.6 1712.84  5692.5 1713.27  5762.5 1713.23  5862.5 1714.03  5923.3 1714.04
#Mann=3,-1,0
  3949.9    0.05       0  4627.8   0.035       0  4632.8    0.05       0
Bank Sta=4627.8,4632.8
Exp/Cntr=0.3,0.1

Type RM Length L Ch R = 1,6698,317,317,317
BEGIN DESCRIPTION:
Mapping XS 4bcc1f14
END DESCRIPTION:
XS GIS Cut Line= 3
      1612056.15      6878697.45      1612147.30      6878753.88
      1614716.78      6878693.12
#Sta/Elev= 30
  3422.4 1713.92  3424.7 1713.92  3429.9 1712.91  3435.8 1712.98  3444.6 1711.80
  3457.1 1711.51  3466.6 1712.99  3472.5 1713.13  3479.9 1712.93  3487.8 1712.12
  3509.1 1712.19  3524.5 1711.81  3528.8 1712.06  3564.6 1712.12  3697.3 1711.83
  3986.1 1712.03  4544.0 1711.21  4544.5 1710.71  4550.7 1710.71  4551.2 1711.21
  4687.6 1711.58  4717.6 1711.37  5077.7 1711.69  5297.8 1712.24  5567.9 1712.29
  5727.9 1712.81  5837.9 1712.77  5928.0 1713.05  6038.0 1713.91  6099.8 1713.95
#Mann=3,-1,0
  3422.4    0.05       0  4544.0    0.03       0  4551.2    0.05       0
Bank Sta=4544,4551.2
Exp/Cntr=0.3,0.1

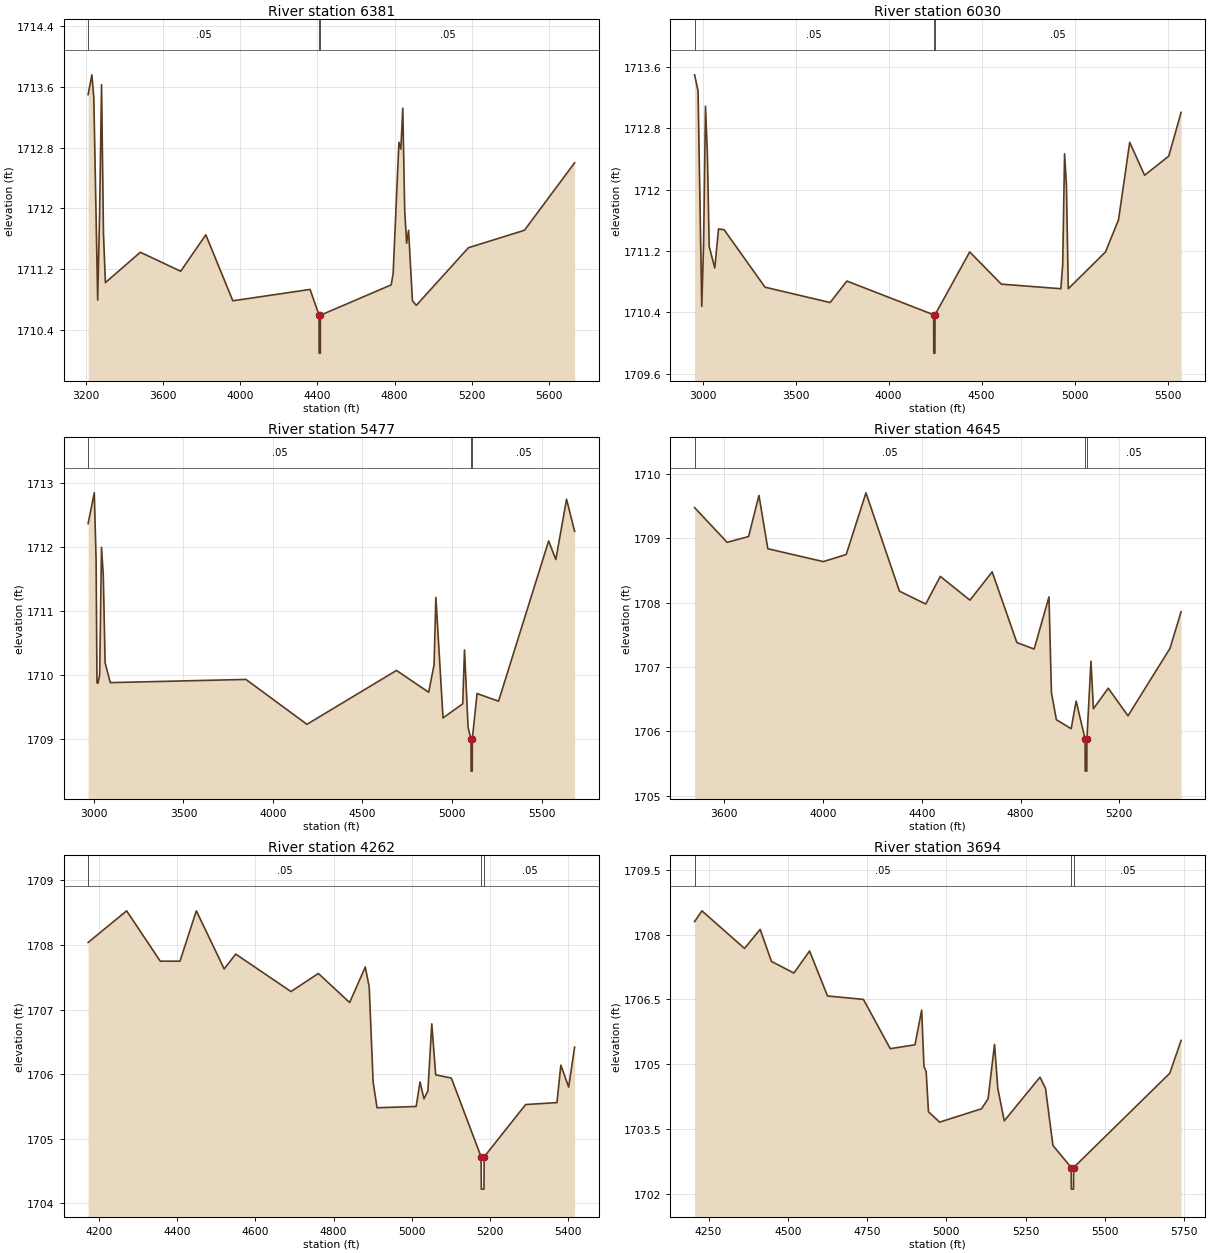
Type RM Length L Ch R = 1,6381,351,351,351
BEGIN DESCRIPTION:
Deadman 57 2.0
END DESCRIPTION:
XS GIS Cut Line= 2
      1612025.52      6878927.12      1614544.92      6878888.13
#Sta/Elev= 30
  3212.7 1713.50  3232.2 1713.76  3242.2 1713.46  3262.2 1710.79  3272.2 1711.92
  3282.2 1713.63  3292.2 1711.67  3302.2 1711.02  3483.1 1711.42  3692.2 1711.17
  3822.3 1711.65  3962.3 1710.78  4362.3 1710.93  4408.7 1710.59  4409.2 1710.09
  4415.4 1710.09  4415.9 1710.59  4782.4 1710.99  4792.4 1711.14  4822.4 1712.87
  4832.4 1712.78  4842.4 1713.32  4852.4 1711.97  4862.4 1711.54  4872.4 1711.71
  4892.4 1710.78  4912.4 1710.72  5182.4 1711.48  5472.5 1711.71  5732.4 1712.60
#Mann=3,-1,0
  3212.7    0.05       0  4408.7   0.035       0  4415.9    0.05       0
Bank Sta=4408.7,4415.9
Exp/Cntr=0.3,0.1

Type RM Length L Ch R = 1,6030,553,553,553
BEGIN DESCRIPTION:
Mapping XS d3f2c797
END DESCRIPTION:
XS GIS Cut Line= 2
      1612036.36      6879093.20      1614651.19      6879055.47
#Sta/Elev= 30
  2957.3 1713.50  2976.0 1713.29  2995.9 1710.48  3005.9 1711.31  3015.9 1713.09
  3025.9 1712.49  3035.9 1711.26  3066.0 1710.98  3086.0 1711.49  3116.0 1711.48
  3336.0 1710.73  3686.0 1710.53  3776.0 1710.81  4242.5 1710.37  4243.0 1709.87
  4249.2 1709.87  4249.7 1710.37  4436.1 1711.19  4606.1 1710.77  4926.1 1710.71
  4936.1 1711.03  4946.1 1712.47  4956.1 1712.06  4966.1 1710.71  5166.2 1711.19
  5236.2 1711.61  5296.2 1712.62  5376.2 1712.19  5506.2 1712.44  5572.4 1713.01
#Mann=3,-1,0
  2957.3    0.05       0  4242.5    0.05       0  4249.7    0.05       0
Bank Sta=4242.5,4249.7
Exp/Cntr=0.3,0.1

Type RM Length L Ch R = 1,5477,832,832,832
BEGIN DESCRIPTION:
Deadman 57 1.4
END DESCRIPTION:
XS GIS Cut Line= 3
      1612020.91      6879486.61      1613000.09      6879613.35
      1614730.05      6879613.00
#Sta/Elev= 30
  2967.6 1712.36  3002.0 1712.84  3012.1 1711.81  3017.2 1709.88  3022.3 1709.87
  3032.2 1710.00  3042.3 1711.99  3052.4 1711.55  3062.5 1710.19  3091.5 1709.88
  3849.0 1709.93  4189.9 1709.23  4689.9 1710.07  4869.9 1709.73  4899.9 1710.16
  4909.9 1711.21  4949.9 1709.33  5059.9 1709.55  5069.9 1710.39  5089.9 1709.18
  5106.2 1709.00  5106.7 1708.50  5113.0 1708.50  5113.5 1709.00  5139.9 1709.71
  5259.9 1709.59  5539.9 1712.09  5579.9 1711.80  5639.9 1712.74  5684.9 1712.24
#Mann=3,-1,0
  2967.6    0.05       0  5106.2    0.05       0  5113.5    0.05       0
Bank Sta=5106.2,5113.5
Exp/Cntr=0.3,0.1

Type RM Length L Ch R = 1,4645,383,383,383
BEGIN DESCRIPTION:
Deadman 57 1.3
END DESCRIPTION:
XS GIS Cut Line= 3
      1612870.72      6879879.00      1613641.60      6880402.19
      1614679.99      6880413.00
#Sta/Elev= 30
  3480.2 1709.48  3612.1 1708.94  3698.9 1709.03  3740.9 1709.67  3776.8 1708.84
  4001.4 1708.64  4094.2 1708.75  4174.2 1709.71  4309.8 1708.18  4416.1 1707.98
  4475.3 1708.41  4595.3 1708.04  4685.3 1708.48  4785.3 1707.38  4855.3 1707.28
  4915.3 1708.09  4925.3 1706.60  4945.3 1706.18  5005.3 1706.04  5025.3 1706.47
  5061.6 1705.88  5062.1 1705.38  5068.5 1705.38  5069.0 1705.88  5085.3 1707.09
  5095.3 1706.35  5155.3 1706.67  5235.3 1706.24  5405.3 1707.29  5450.3 1707.86
#Mann=3,-1,0
  3480.2    0.05       0  5061.6    0.05       0  5069.0    0.05       0
Bank Sta=5061.6,5069
Exp/Cntr=0.3,0.1

Type RM Length L Ch R = 1,4262,568,568,568
BEGIN DESCRIPTION:
Mapping XS a5cc427f
END DESCRIPTION:
XS GIS Cut Line= 3
      1613532.67      6880543.63      1613864.57      6880781.29
      1614700.21      6880773.10
#Sta/Elev= 30
  4172.2 1708.04  4270.7 1708.53  4356.7 1707.75  4407.1 1707.75  4448.9 1708.53
  4520.1 1707.63  4549.6 1707.86  4690.9 1707.28  4760.9 1707.56  4840.9 1707.11
  4880.9 1707.66  4890.9 1707.35  4900.9 1705.88  4910.9 1705.48  5010.9 1705.50
  5020.9 1705.88  5030.9 1705.62  5040.9 1705.74  5050.9 1706.78  5060.9 1705.99
  5100.9 1705.94  5177.0 1704.72  5177.5 1704.22  5184.3 1704.22  5184.8 1704.72
  5290.9 1705.53  5370.9 1705.56  5380.9 1706.14  5400.9 1705.80  5416.1 1706.42
#Mann=3,-1,0
  4172.2    0.05       0  5177.0    0.05       0  5184.8    0.05       0
Bank Sta=5177,5184.8
Exp/Cntr=0.3,0.1

Type RM Length L Ch R = 1,3694,962,962,962
BEGIN DESCRIPTION:
Deadman 57 1.2
END DESCRIPTION:
XS GIS Cut Line= 3
      1613460.70      6880629.78      1614006.41      6881206.38
      1614729.96      6881362.99
#Sta/Elev= 30
  4206.1 1708.30  4229.2 1708.55  4363.6 1707.68  4412.9 1708.12  4448.5 1707.38
  4519.3 1707.11  4568.7 1707.62  4625.3 1706.58  4738.6 1706.50  4823.2 1705.36
  4901.2 1705.45  4922.2 1706.25  4929.5 1704.95  4936.4 1704.83  4943.7 1703.90
  4978.9 1703.66  5111.1 1703.97  5131.6 1704.20  5152.0 1705.46  5162.3 1704.44
  5182.7 1703.69  5295.3 1704.70  5312.8 1704.44  5336.2 1703.12  5393.7 1702.61
  5394.2 1702.11  5401.0 1702.11  5401.5 1702.61  5704.5 1704.79  5740.3 1705.55
#Mann=3,-1,0
  4206.1    0.05       0  5393.7    0.05       0  5401.5    0.05       0
Bank Sta=5393.7,5401.5
Exp/Cntr=0.3,0.1

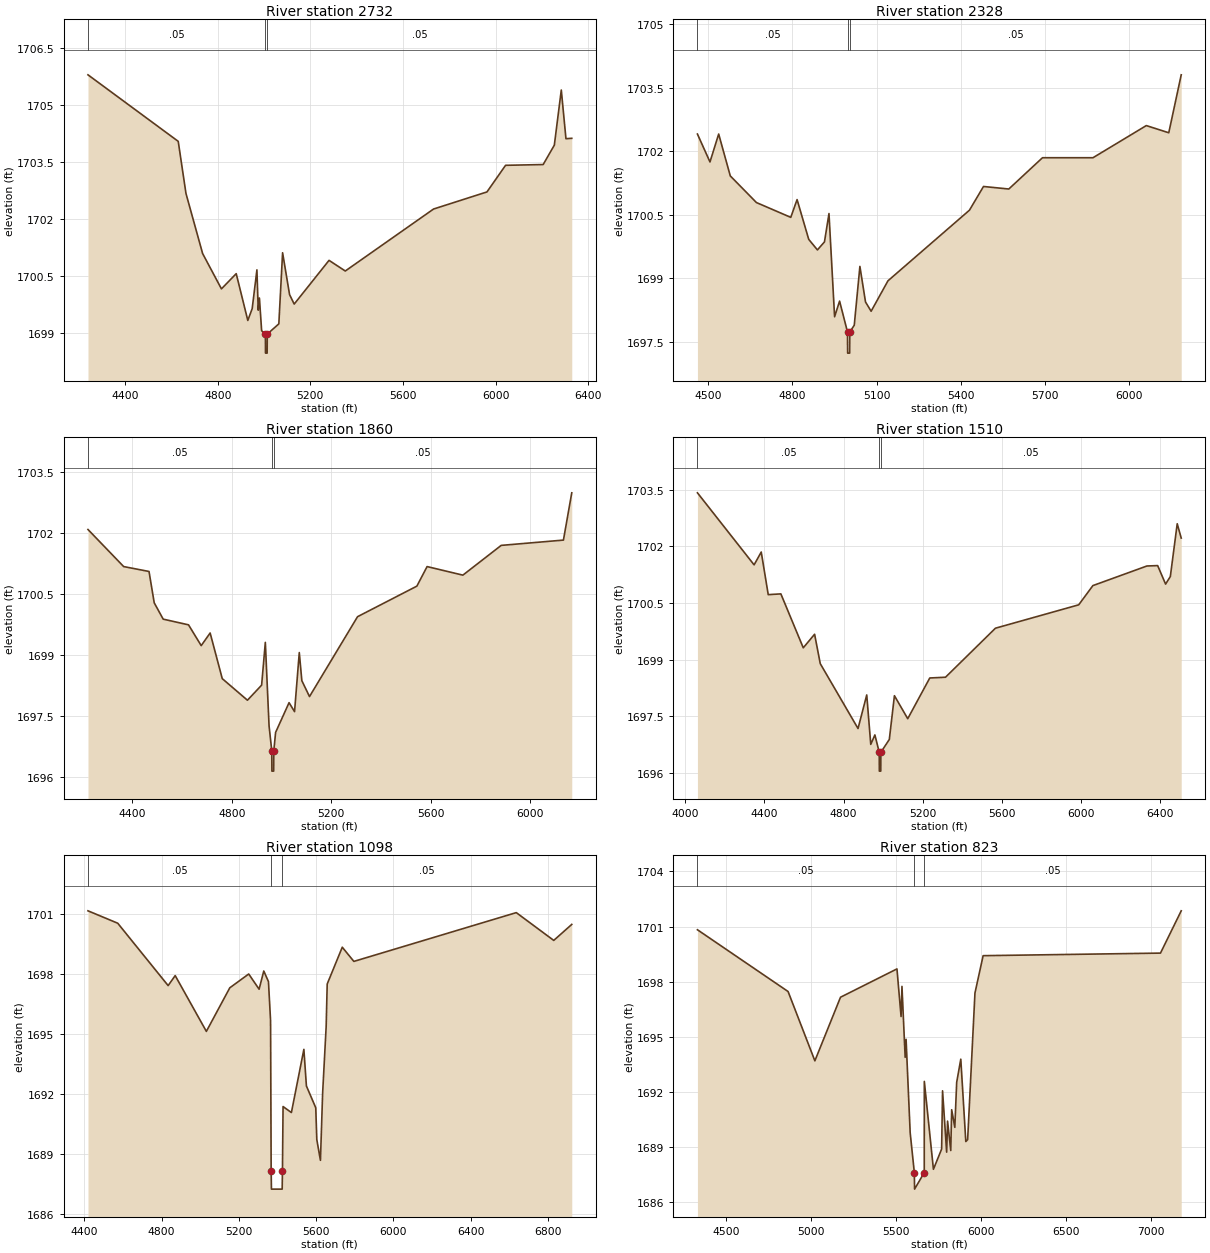
Type RM Length L Ch R = 1,2732,404,404,404
BEGIN DESCRIPTION:
Deadman 57 1.1
END DESCRIPTION:
XS GIS Cut Line= 3
      1612710.71      6881713.09      1613455.07      6881867.97
      1614780.02      6881763.00
#Sta/Elev= 30
  4239.7 1705.80  4629.5 1704.05  4662.9 1702.68  4734.8 1701.10  4816.1 1700.17
  4879.9 1700.57  4930.0 1699.34  4948.9 1699.65  4969.3 1700.67  4975.0 1699.61
  4980.1 1699.93  4989.7 1699.07  5005.9 1698.98  5006.4 1698.48  5013.5 1698.48
  5014.0 1698.98  5064.0 1699.25  5080.2 1701.12  5110.3 1700.02  5130.3 1699.77
  5280.8 1700.92  5351.0 1700.64  5732.2 1702.27  5962.9 1702.72  6043.2 1703.42
  6205.6 1703.44  6253.8 1703.95  6283.9 1705.40  6304.0 1704.12  6329.1 1704.13
#Mann=3,-1,0
  4239.7    0.05       0  5005.9    0.05       0  5014.0    0.05       0
Bank Sta=5005.9,5014
Exp/Cntr=0.3,0.1

Type RM Length L Ch R = 1,2328,468,468,468
BEGIN DESCRIPTION:
Mapping XS aacc8172
END DESCRIPTION:
XS GIS Cut Line= 4
      1613031.85      6882126.04      1613478.24      6882245.61
      1614202.60      6882205.55      1614739.41      6882195.61
#Sta/Elev= 30
  4461.3 1702.41  4506.0 1701.75  4537.0 1702.41  4578.4 1701.42  4671.6 1700.79
  4794.0 1700.44  4816.5 1700.86  4858.0 1699.92  4889.0 1699.67  4914.1 1699.86
  4930.2 1700.53  4950.2 1698.09  4968.0 1698.46  4996.2 1697.73  4996.7 1697.23
  5003.9 1697.23  5004.4 1697.73  5020.3 1697.89  5040.4 1699.28  5060.4 1698.44
  5080.4 1698.22  5140.5 1698.94  5431.0 1700.61  5481.0 1701.17  5571.2 1701.11
  5691.3 1701.85  5871.3 1701.85  6061.4 1702.61  6141.4 1702.44  6185.8 1703.81
#Mann=3,-1,0
  4461.3    0.05       0  4996.2    0.05       0  5004.4    0.05       0
Bank Sta=4996.2,5004.4
Exp/Cntr=0.3,0.1

Type RM Length L Ch R = 1,1860,350,350,350
BEGIN DESCRIPTION:
Mapping XS 4005f94a
END DESCRIPTION:
XS GIS Cut Line= 3
      1612947.30      6882285.31      1613575.81      6882708.94
      1614731.00      6882434.89
#Sta/Elev= 30
  4222.1 1702.08  4365.6 1701.17  4467.5 1701.05  4488.5 1700.28  4524.5 1699.88
  4626.4 1699.74  4677.4 1699.23  4713.3 1699.54  4762.0 1698.42  4863.3 1697.89
  4920.3 1698.26  4935.2 1699.31  4950.2 1697.26  4961.1 1696.65  4961.6 1696.15
  4968.8 1696.15  4969.3 1696.65  4976.5 1697.10  5030.6 1697.83  5052.7 1697.61
  5071.7 1699.06  5082.0 1698.37  5112.8 1697.98  5306.0 1699.94  5544.5 1700.69
  5585.6 1701.17  5729.5 1700.96  5883.6 1701.69  6133.8 1701.82  6167.3 1702.98
#Mann=3,-1,0
  4222.1    0.05       0  4961.1    0.05       0  4969.3    0.05       0
Bank Sta=4961.1,4969.3
Exp/Cntr=0.3,0.1

Type RM Length L Ch R = 1,1510,412,412,412
BEGIN DESCRIPTION:
Mapping XS eac2c34c
END DESCRIPTION:
XS GIS Cut Line= 4
      1612697.81      6882301.68      1613194.72      6882890.94
      1613590.50      6883005.27      1614754.99      6882523.73
#Sta/Elev= 30
  4062.0 1703.42  4348.1 1701.51  4384.2 1701.85  4419.5 1700.72  4483.3 1700.74
  4596.4 1699.31  4653.6 1699.67  4682.2 1698.89  4872.9 1697.17  4916.9 1698.06
  4937.2 1696.75  4958.0 1697.00  4980.0 1696.54  4980.5 1696.04  4987.8 1696.04
  4988.3 1696.54  5030.9 1696.88  5056.7 1698.04  5123.9 1697.43  5235.2 1698.51
  5314.6 1698.53  5566.8 1699.83  5987.2 1700.45  6058.9 1700.96  6331.8 1701.48
  6385.9 1701.49  6426.0 1701.00  6449.9 1701.20  6484.7 1702.60  6504.9 1702.22
#Mann=3,-1,0
  4062.0    0.05       0  4980.0    0.05       0  4988.3    0.05       0
Bank Sta=4980,4988.3
Exp/Cntr=0.3,0.1

Type RM Length L Ch R = 1,1098,275,275,275
BEGIN DESCRIPTION:
Mapping XS 3b70eb46
END DESCRIPTION:
XS GIS Cut Line= 3
      1612721.63      6882677.67      1613117.48      6883306.17
      1614751.47      6882650.49
#Sta/Elev= 30
  4419.5 1701.15  4573.5 1700.53  4834.3 1697.41  4870.8 1697.91  5032.1 1695.12
  5153.4 1697.30  5251.3 1697.99  5305.0 1697.23  5329.2 1698.14  5353.4 1697.61
  5364.3 1695.66  5367.4 1688.13  5368.8 1687.23  5424.4 1687.23  5425.8 1688.13
  5429.0 1691.36  5472.1 1691.06  5536.7 1694.22  5549.8 1692.39  5598.2 1691.30
  5603.6 1689.71  5622.4 1688.67  5633.7 1692.02  5652.0 1695.36  5657.4 1697.49
  5735.4 1699.33  5795.3 1698.62  6635.8 1701.06  6829.7 1699.67  6922.9 1700.47
#Mann=3,-1,0
  4419.5    0.05       0  5367.4   0.035       0  5425.8    0.05       0
Bank Sta=5367.4,5425.8
Exp/Cntr=0.3,0.1

Type RM Length L Ch R = 1,823,0,0,0
BEGIN DESCRIPTION:
Deadman 57 1.0
END DESCRIPTION:
XS GIS Cut Line= 4
      1612508.71      6882719.46      1612798.94      6883317.50
      1612913.00      6883456.23      1614770.96      6882706.42
#Sta/Elev= 30
  4332.4 1700.83  4866.0 1697.47  5023.7 1693.70  5174.7 1697.16  5506.9 1698.70
  5531.1 1696.11  5536.4 1697.75  5555.2 1693.89  5560.6 1694.87  5584.7 1689.79
  5609.2 1687.62  5610.6 1686.72  5667.6 1687.62  5668.0 1692.58  5721.6 1687.80
  5769.9 1688.90  5775.3 1692.07  5799.5 1688.73  5804.8 1690.42  5823.6 1688.82
  5829.0 1691.04  5847.5 1690.08  5858.5 1692.53  5882.7 1693.79  5912.2 1689.31
  5923.0 1689.41  5966.1 1697.39  6014.2 1699.42  7058.2 1699.56  7180.3 1701.86
#Mann=3,-1,0
  4332.4    0.05       0  5609.2   0.035       0  5667.6    0.05       0
Bank Sta=5609.2,5667.6
Exp/Cntr=0.3,0.1

Chan Stop Cuts=-1