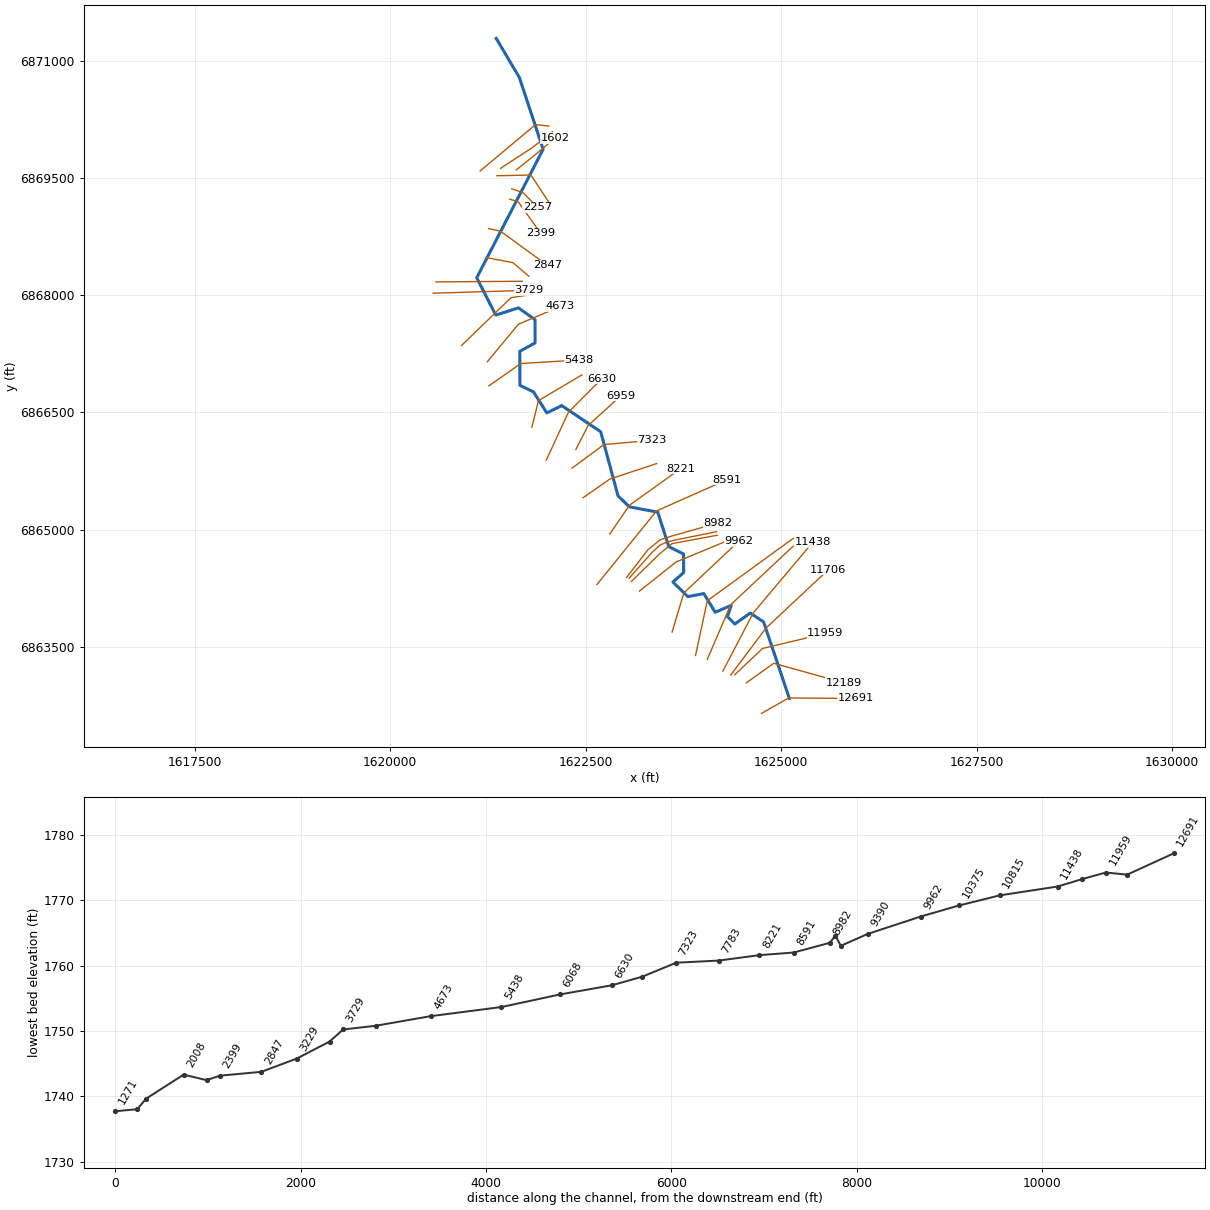
--- Deadman 58.prj (project) ---

Proj Title=Deadman 58 Base Level Engineering
Current Plan=p01
Default Exp/Contr=0.3,0.1
English Units
Geom File=g01
Flow File=f01
Plan File=p01
BEGIN DESCRIPTION:
Deadman 58
END DESCRIPTION:

--- Deadman 58.p01 (plan) ---

Plan Title=Multiple Run
Short Identifier=Multiple
Geom File=g01
Flow File=f01
Subcritical Flow
K Sum by GR= 0
Std Step Tol= 0.01
Critical Tol= 0.01
Num of Std Step Trials= 20
Max Error Tol= 0.3
Flow Tol Ratio= 0.001
Split Flow NTrial= 30
Split Flow Tol= 0.02
Split Flow Ratio= 0.02
Log Output Level= 0
Friction Slope Method= 1
Unsteady Friction Slope Method= 2
Unsteady Bridges Friction Slope Method= 1
Parabolic Critical Depth
Global Vel Dist=  1 , 1 , 1
Global Log Level= 0
CheckData=True
Encroach Param= -1, 0, 0, 0
BEGIN DESCRIPTION:
Multiple Run
END DESCRIPTION:

--- Deadman 58.f01 (steady flow) ---

Flow Title=Multiple
Number of Profiles=7
Profile Names=10-year,25-year,50-year,1pct_min,100-year,1pct_plu,500-year
River Rch & RM= Deadman 58,Reach-1,12691
     183     248     300     181     362     721     530
River Rch & RM= Deadman 58,Reach-1,12189
     269     370     453     275     550    1096     821
River Rch & RM= Deadman 58,Reach-1,3583
     272     374     457     278     555    1107     827
Boundary for River Rch & Prof#=Deadman 58,Reach-1,1
Up Type=0
Dn Type=3
Dn Slope=0.009
Boundary for River Rch & Prof#=Deadman 58,Reach-1,2
Up Type=0
Dn Type=3
Dn Slope=0.009
Boundary for River Rch & Prof#=Deadman 58,Reach-1,3
Up Type=0
Dn Type=3
Dn Slope=0.009
Boundary for River Rch & Prof#=Deadman 58,Reach-1,4
Up Type=0
Dn Type=3
Dn Slope=0.009
Boundary for River Rch & Prof#=Deadman 58,Reach-1,5
Up Type=0
Dn Type=3
Dn Slope=0.009
Boundary for River Rch & Prof#=Deadman 58,Reach-1,6
Up Type=0
Dn Type=3
Dn Slope=0.009
Boundary for River Rch & Prof#=Deadman 58,Reach-1,7
Up Type=0
Dn Type=3
Dn Slope=0.009

--- Deadman 58.g01 (geometry) ---

Geom Title=Existing Conditions

River Reach=Deadman 58,Reach-1
Reach XY= 30
      1625105.00      6862838.00      1624775.52      6863818.28
      1624604.91      6863930.72      1624406.62      6863791.10
      1624312.60      6863884.65      1624361.83      6864030.24
      1624156.79      6863940.86      1624011.06      6864180.73
      1623806.47      6864141.53      1623615.95      6864328.01
      1623753.37      6864449.83      1623751.56      6864686.78
      1623562.68      6864781.48      1623422.14      6865221.55
      1623056.46      6865291.54      1622913.14      6865431.94
      1622691.74      6866251.66      1622192.96      6866586.85
      1622002.46      6866492.96      1621832.14      6866761.84
      1621658.06      6866846.28      1621656.96      6867282.13
      1621851.46      6867389.00      1621851.47      6867686.55
      1621639.78      6867837.51      1621348.95      6867745.46
      1621105.37      6868222.83      1621954.95      6869867.96
      1621651.17      6870786.42      1621355.00      6871288.00

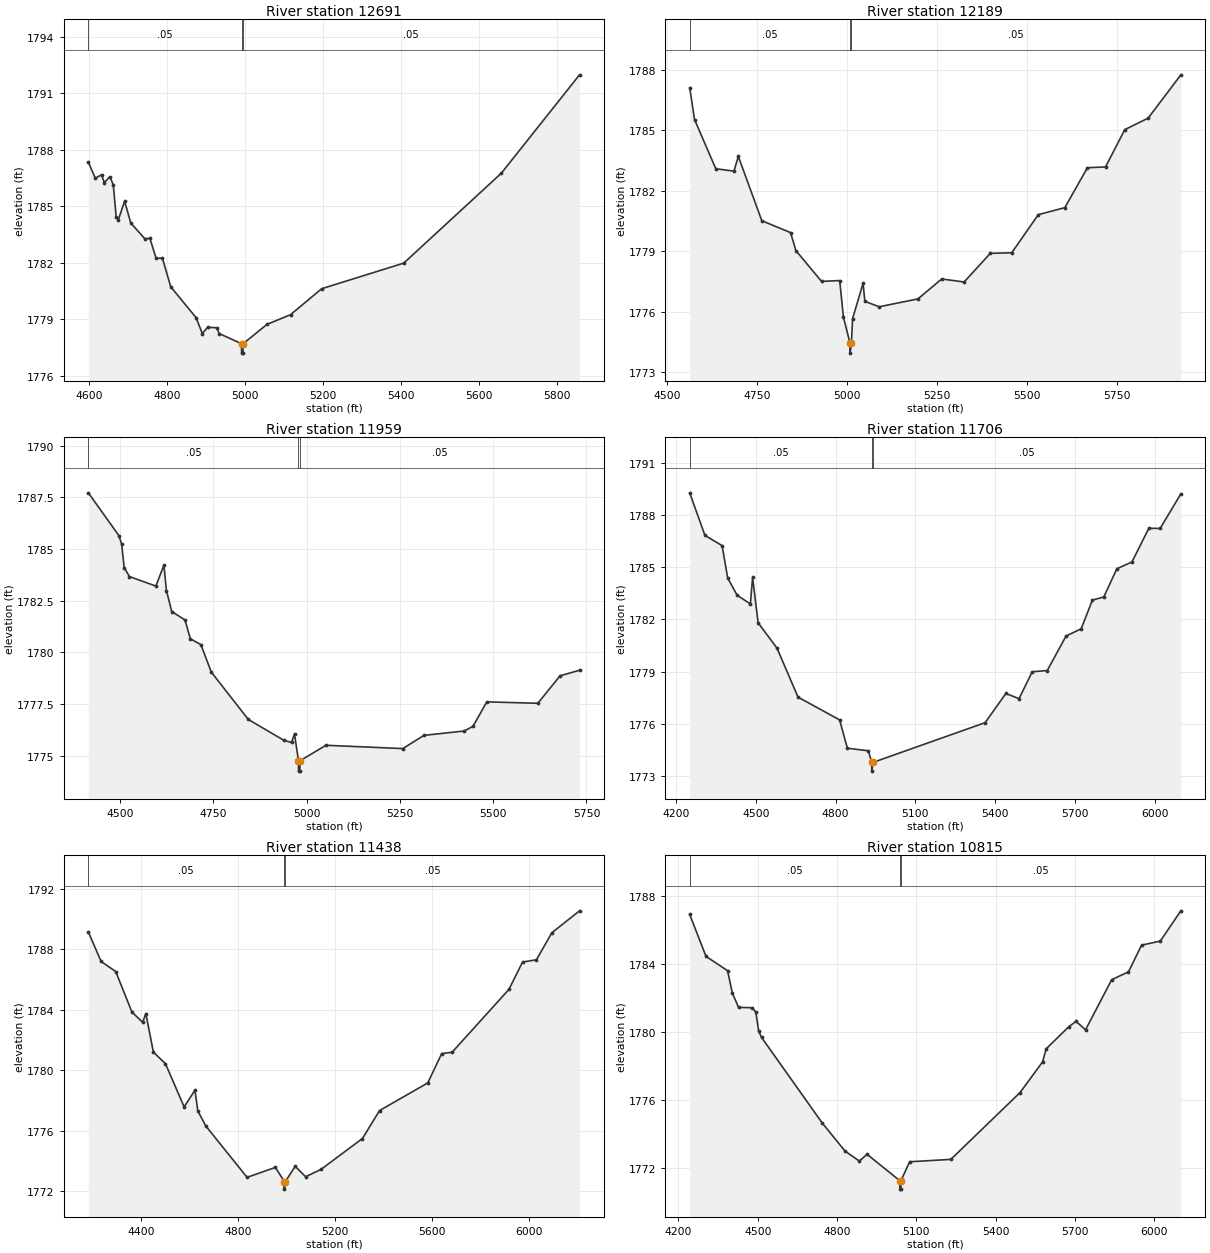
Type RM Length L Ch R = 1,12691,502,502,502
BEGIN DESCRIPTION:
Deadman 58 12.0
END DESCRIPTION:
XS GIS Cut Line= 3
      1624749.42      6862647.08      1625097.16      6862844.54
      1625955.04      6862838.00
#Sta/Elev= 30
  4598.9 1787.33  4616.8 1786.48  4632.6 1786.66  4639.8 1786.25  4654.2 1786.56
  4662.8 1786.12  4670.1 1784.43  4675.9 1784.28  4691.7 1785.26  4707.6 1784.10
  4743.3 1783.27  4756.6 1783.28  4772.5 1782.22  4788.4 1782.24  4810.0 1780.71
  4874.9 1779.07  4890.7 1778.23  4904.3 1778.56  4927.3 1778.54  4934.0 1778.23
  4991.1 1777.69  4991.4 1777.19  4994.9 1777.19  4995.1 1777.69  5056.6 1778.72
  5116.6 1779.23  5196.3 1780.61  5406.6 1781.97  5656.7 1786.75  5856.7 1791.97
#Mann=3,-1,0
  4598.9    0.05       0  4991.1    0.05       0  4995.1    0.05       0
Bank Sta=4991.1,4995.1
Exp/Cntr=0.3,0.1

Type RM Length L Ch R = 1,12189,230,230,230
BEGIN DESCRIPTION:
Deadman 58 11.0
END DESCRIPTION:
XS GIS Cut Line= 3
      1624555.03      6863038.02      1624905.00      6863288.00
      1625805.04      6863037.99
#Sta/Elev= 30
  4563.1 1787.11  4576.6 1785.53  4635.6 1783.09  4686.0 1782.97  4698.2 1783.70
  4763.4 1780.51  4843.3 1779.92  4858.0 1779.03  4929.3 1777.50  4979.7 1777.54
  4990.1 1775.73  5008.3 1774.44  5008.6 1773.94  5012.3 1774.44  5015.5 1775.65
  5044.6 1777.40  5049.7 1776.51  5089.2 1776.24  5197.1 1776.63  5263.0 1777.62
  5325.3 1777.47  5397.9 1778.89  5457.6 1778.92  5531.3 1780.81  5605.0 1781.16
  5667.8 1783.14  5718.1 1783.18  5771.6 1785.03  5836.4 1785.60  5927.3 1787.75
#Mann=3,-1,0
  4563.1    0.05       0  5008.3    0.05       0  5012.3    0.05       0
Bank Sta=5008.3,5012.3
Exp/Cntr=0.3,0.1

Type RM Length L Ch R = 1,11959,253,253,253
BEGIN DESCRIPTION:
Mapping XS 84a2fad4
END DESCRIPTION:
XS GIS Cut Line= 3
      1624405.53      6863141.41      1624762.92      6863478.08
      1625565.68      6863669.71
#Sta/Elev= 30
  4415.0 1787.72  4496.9 1785.65  4504.2 1785.24  4511.1 1784.10  4525.2 1783.67
  4596.0 1783.21  4617.5 1784.22  4624.3 1782.99  4638.5 1781.98  4674.1 1781.57
  4688.3 1780.66  4716.5 1780.38  4744.5 1779.05  4843.6 1776.76  4939.0 1775.75
  4959.5 1775.65  4967.5 1776.06  4978.1 1774.76  4978.3 1774.26  4981.8 1774.26
  4982.1 1774.76  5051.7 1775.51  5257.7 1775.35  5314.5 1775.99  5422.2 1776.20
  5445.9 1776.43  5482.9 1777.61  5619.5 1777.54  5679.2 1778.87  5731.3 1779.14
#Mann=3,-1,0
  4415.0    0.05       0  4978.1    0.03       0  4982.1    0.05       0
Bank Sta=4978.1,4982.1
Exp/Cntr=0.3,0.1

Type RM Length L Ch R = 1,11706,268,268,268
BEGIN DESCRIPTION:
Deadman 58 10.0
END DESCRIPTION:
XS GIS Cut Line= 3
      1624354.97      6863137.96      1624805.00      6863738.00
      1625604.97      6864487.98
#Sta/Elev= 30
  4251.4 1789.29  4308.7 1786.84  4373.3 1786.25  4394.2 1784.39  4429.6 1783.40
  4479.6 1782.89  4487.9 1784.42  4508.7 1781.81  4579.6 1780.35  4658.7 1777.53
  4815.0 1776.22  4844.2 1774.59  4923.3 1774.44  4935.7 1773.77  4936.0 1773.27
  4940.2 1773.77  5362.2 1776.06  5440.1 1777.74  5489.7 1777.44  5539.0 1778.99
  5595.7 1779.06  5666.5 1781.05  5723.1 1781.46  5765.6 1783.12  5808.1 1783.29
  5857.5 1784.92  5914.1 1785.31  5977.6 1787.25  6020.1 1787.24  6098.0 1789.23
#Mann=3,-1,0
  4251.4    0.05       0  4935.7    0.05       0  4940.2    0.05       0
Bank Sta=4935.7,4940.2
Exp/Cntr=0.3,0.1

Type RM Length L Ch R = 1,11438,623,623,623
BEGIN DESCRIPTION:
Deadman 58 9.0
END DESCRIPTION:
XS GIS Cut Line= 3
      1624254.99      6863187.97      1624641.98      6863931.79
      1625404.98      6864837.98
#Sta/Elev= 30
  4183.1 1789.14  4235.6 1787.19  4295.9 1786.52  4362.6 1783.84  4406.8 1783.16
  4419.9 1783.74  4451.0 1781.19  4500.8 1780.42  4577.7 1777.56  4622.2 1778.67
  4634.0 1777.30  4666.4 1776.31  4836.9 1772.90  4953.8 1773.56  4990.1 1772.62
  4990.4 1772.12  4994.6 1772.62  5035.1 1773.63  5078.0 1772.94  5141.7 1773.43
  5312.1 1775.47  5382.6 1777.32  5581.3 1779.15  5638.5 1781.09  5681.4 1781.18
  5915.5 1785.34  5971.5 1787.15  6028.7 1787.30  6092.4 1789.09  6206.2 1790.54
#Mann=3,-1,0
  4183.1    0.05       0  4990.1    0.05       0  4994.6    0.05       0
Bank Sta=4990.1,4994.6
Exp/Cntr=0.3,0.1

Type RM Length L Ch R = 1,10815,440,440,440
BEGIN DESCRIPTION:
Deadman 58 8.0
END DESCRIPTION:
XS GIS Cut Line= 3
      1624054.99      6863337.97      1624355.00      6864038.00
      1625155.00      6864788.00
#Sta/Elev= 30
  4242.5 1786.93  4304.2 1784.46  4385.8 1783.62  4403.9 1782.30  4427.5 1781.46
  4480.1 1781.44  4492.8 1781.16  4503.6 1780.06  4514.5 1779.69  4743.0 1774.68
  4830.0 1773.01  4884.4 1772.42  4913.4 1772.82  5037.2 1771.27  5037.6 1770.77
  5041.5 1770.77  5041.8 1771.27  5074.7 1772.38  5230.5 1772.52  5492.3 1776.45
  5577.3 1778.25  5591.5 1779.03  5676.0 1780.31  5704.3 1780.64  5740.0 1780.14
  5839.1 1783.09  5902.6 1783.55  5952.0 1785.12  6022.8 1785.36  6100.7 1787.14
#Mann=3,-1,0
  4242.5    0.05       0  5037.2    0.03       0  5041.8    0.05       0
Bank Sta=5037.2,5041.8
Exp/Cntr=0.3,0.1

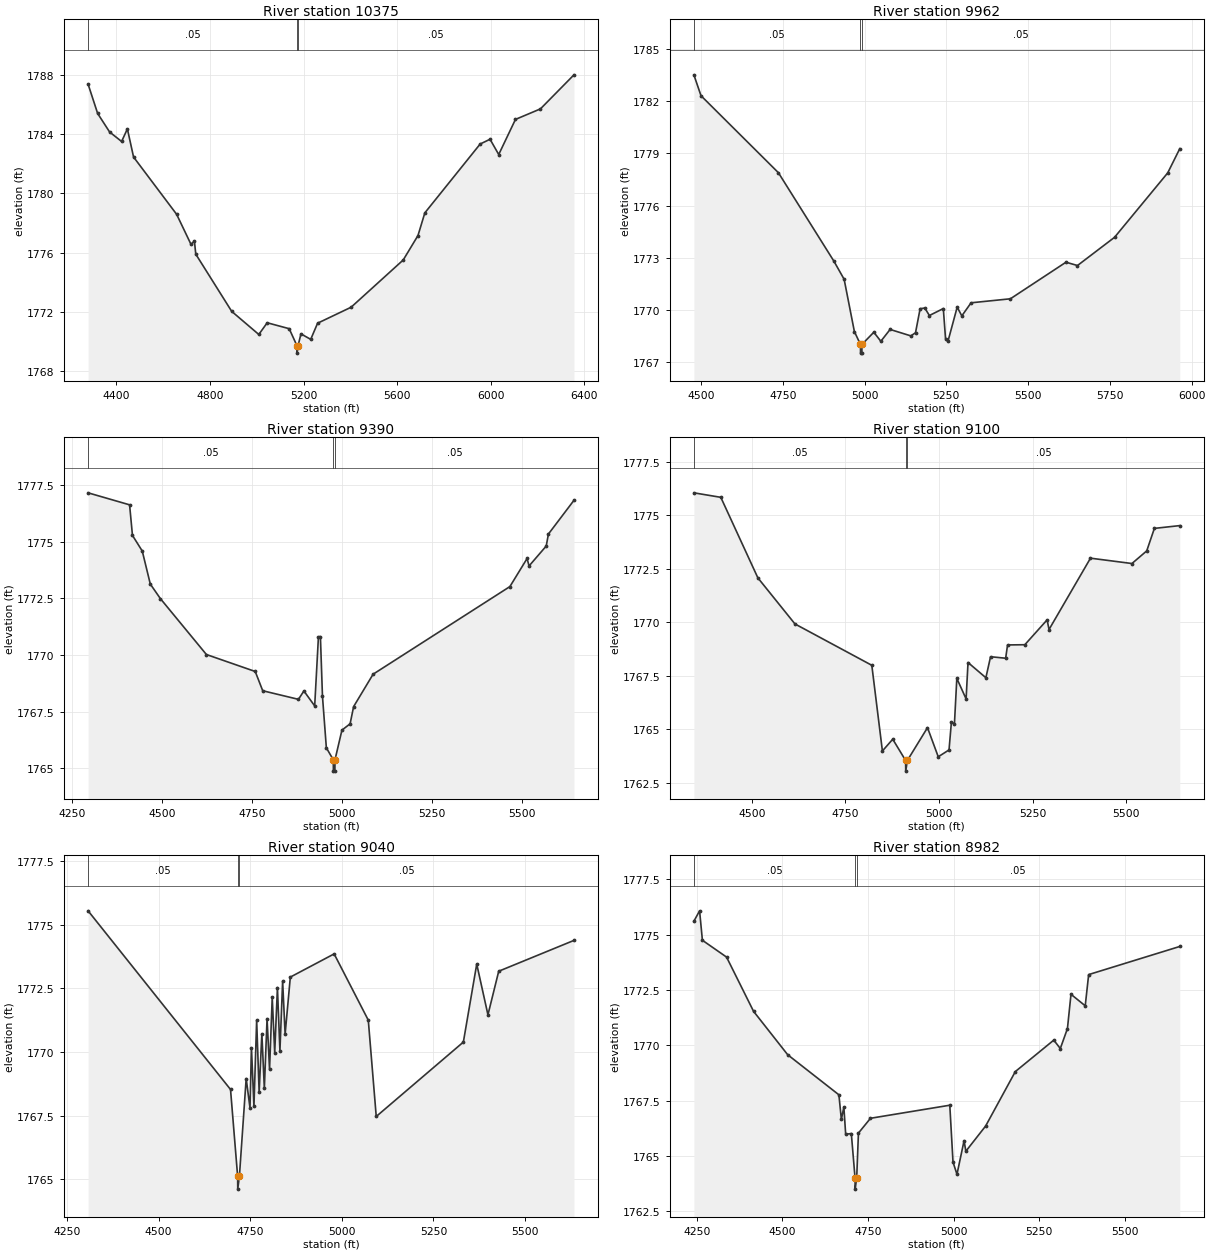
Type RM Length L Ch R = 1,10375,413,413,413
BEGIN DESCRIPTION:
Deadman 58 7.0
END DESCRIPTION:
XS GIS Cut Line= 3
      1623905.00      6863388.01      1624055.00      6864088.00
      1625154.98      6864887.98
#Sta/Elev= 30
  4279.2 1787.38  4320.1 1785.40  4371.2 1784.15  4422.4 1783.51  4447.1 1784.36
  4473.5 1782.46  4657.6 1778.59  4719.0 1776.56  4733.4 1776.79  4739.4 1775.90
  4892.8 1772.04  5008.6 1770.48  5044.5 1771.27  5138.4 1770.87  5171.7 1769.72
  5172.0 1769.22  5176.3 1769.72  5188.7 1770.52  5230.4 1770.15  5259.8 1771.24
  5403.1 1772.32  5625.7 1775.51  5688.7 1777.16  5718.0 1778.69  5954.5 1783.34
  5996.6 1783.66  6033.7 1782.63  6105.2 1785.00  6211.9 1785.71  6355.2 1788.01
#Mann=3,-1,0
  4279.2    0.05       0  5171.7    0.03       0  5176.3    0.05       0
Bank Sta=5171.7,5176.3
Exp/Cntr=0.3,0.1

Type RM Length L Ch R = 1,9962,572,572,572
BEGIN DESCRIPTION:
Deadman 58 6.0
END DESCRIPTION:
XS GIS Cut Line= 3
      1623605.00      6863687.99      1623755.00      6864188.00
      1624456.09      6864848.87
#Sta/Elev= 30
  4478.3 1783.51  4500.1 1782.31  4736.7 1777.89  4906.4 1772.81  4937.7 1771.77
  4969.0 1768.77  4987.5 1768.03  4987.9 1767.53  4991.9 1767.53  4992.2 1768.03
  5028.4 1768.73  5049.9 1768.21  5078.2 1768.89  5141.7 1768.52  5155.9 1768.70
  5170.0 1770.08  5184.2 1770.12  5198.4 1769.69  5240.9 1770.09  5247.7 1768.36
  5255.0 1768.20  5283.3 1770.17  5297.5 1769.67  5325.8 1770.42  5446.0 1770.65
  5615.9 1772.75  5651.1 1772.56  5764.4 1774.18  5927.0 1777.88  5963.8 1779.27
#Mann=3,-1,0
  4478.3    0.05       0  4987.5    0.05       0  4992.2    0.05       0
Bank Sta=4987.5,4992.2
Exp/Cntr=0.3,0.1

Type RM Length L Ch R = 1,9390,290,290,290
BEGIN DESCRIPTION:
Mapping XS 2053e5a7
END DESCRIPTION:
XS GIS Cut Line= 3
      1623187.90      6864212.71      1623654.68      6864584.48
      1624350.61      6864872.74
#Sta/Elev= 30
  4294.1 1777.16  4409.4 1776.63  4417.4 1775.28  4444.6 1774.59  4467.0 1773.13
  4494.9 1772.49  4622.8 1770.02  4758.5 1769.27  4779.3 1768.42  4878.6 1768.04
  4893.7 1768.41  4923.7 1767.75  4934.1 1770.80  4939.6 1770.81  4945.3 1768.18
  4956.1 1765.90  4975.4 1765.37  4975.7 1764.87  4979.8 1764.87  4980.1 1765.37
  4999.4 1766.68  5022.1 1766.96  5031.9 1767.72  5086.0 1769.15  5466.1 1773.02
  5513.8 1774.26  5519.3 1773.93  5567.0 1774.81  5573.1 1775.34  5644.1 1776.83
#Mann=3,-1,0
  4294.1    0.05       0  4975.4    0.05       0  4980.1    0.05       0
Bank Sta=4975.4,4980.1
Exp/Cntr=0.3,0.1

Type RM Length L Ch R = 1,9100,60,60,60
BEGIN DESCRIPTION:
Mapping XS 3654a588
END DESCRIPTION:
XS GIS Cut Line= 4
      1623084.60      6864336.62      1623456.39      6864700.15
      1623605.11      6864819.95      1624181.70      6864927.03
#Sta/Elev= 30
  4345.4 1776.04  4417.3 1775.83  4516.3 1772.07  4615.3 1769.92  4820.5 1767.99
  4848.8 1763.99  4876.4 1764.54  4910.7 1763.55  4911.1 1763.05  4915.5 1763.55
  4969.2 1765.08  4997.9 1763.72  5026.7 1764.04  5033.1 1765.35  5041.1 1765.24
  5047.5 1767.38  5072.3 1766.42  5077.4 1768.12  5125.1 1767.41  5137.6 1768.39
  5177.9 1768.32  5183.0 1768.94  5229.1 1768.95  5288.6 1770.11  5293.7 1769.66
  5404.4 1772.99  5515.1 1772.74  5554.6 1773.33  5575.0 1774.38  5642.8 1774.51
#Mann=3,-1,0
  4345.4    0.05       0  4910.7    0.05       0  4915.5    0.05       0
Bank Sta=4910.7,4915.5
Exp/Cntr=0.3,0.1

Type RM Length L Ch R = 1,9040,58,58,58
BEGIN DESCRIPTION:
Mapping XS 9bcab918
END DESCRIPTION:
XS GIS Cut Line= 6
      1623055.69      6864377.94      1623348.99      6864708.41
      1623452.26      6864803.42      1623543.14      6864840.60
      1623642.28      6864865.39      1624175.20      6864972.80
#Sta/Elev= 30
  4307.3 1775.54  4696.1 1768.53  4715.5 1765.12  4715.8 1764.62  4720.3 1765.12
  4738.8 1768.96  4749.2 1767.81  4753.2 1770.17  4760.0 1767.87  4767.4 1771.25
  4774.2 1768.42  4781.6 1770.72  4788.4 1768.57  4795.8 1771.31  4802.6 1769.32
  4809.9 1772.14  4816.7 1769.97  4824.1 1772.53  4830.9 1770.04  4838.3 1772.78
  4845.1 1770.70  4859.3 1772.94  4978.9 1773.85  5072.1 1771.25  5093.8 1767.47
  5331.6 1770.39  5368.1 1773.45  5398.7 1771.46  5428.1 1773.17  5633.5 1774.38
#Mann=3,-1,0
  4307.3    0.05       0  4715.5    0.05       0  4720.3    0.05       0
Bank Sta=4715.5,4720.3
Exp/Cntr=0.3,0.1

Type RM Length L Ch R = 1,8982,391,391,391
BEGIN DESCRIPTION:
Mapping XS 447d39be
END DESCRIPTION:
XS GIS Cut Line= 5
      1623022.63      6864386.18      1623295.28      6864741.46
      1623452.26      6864869.52      1623621.63      6864923.22
      1624190.82      6865084.08
#Sta/Elev= 30
  4241.4 1775.61  4258.1 1776.08  4266.3 1774.75  4336.9 1773.99  4415.8 1771.54
  4515.5 1769.58  4665.1 1767.77  4672.3 1766.66  4679.6 1767.22  4684.9 1765.99
  4701.4 1766.02  4712.3 1764.01  4712.6 1763.51  4717.1 1764.01  4722.2 1766.04
  4757.4 1766.71  4989.1 1767.30  4998.5 1764.73  5010.1 1764.18  5030.8 1765.70
  5036.0 1765.22  5093.8 1766.36  5180.6 1768.82  5292.9 1770.24  5312.0 1769.86
  5332.8 1770.76  5343.2 1772.31  5384.8 1771.79  5394.8 1773.20  5661.0 1774.47
#Mann=3,-1,0
  4241.4    0.05       0  4712.3    0.05       0  4717.1    0.05       0
Bank Sta=4712.3,4717.1
Exp/Cntr=0.3,0.1

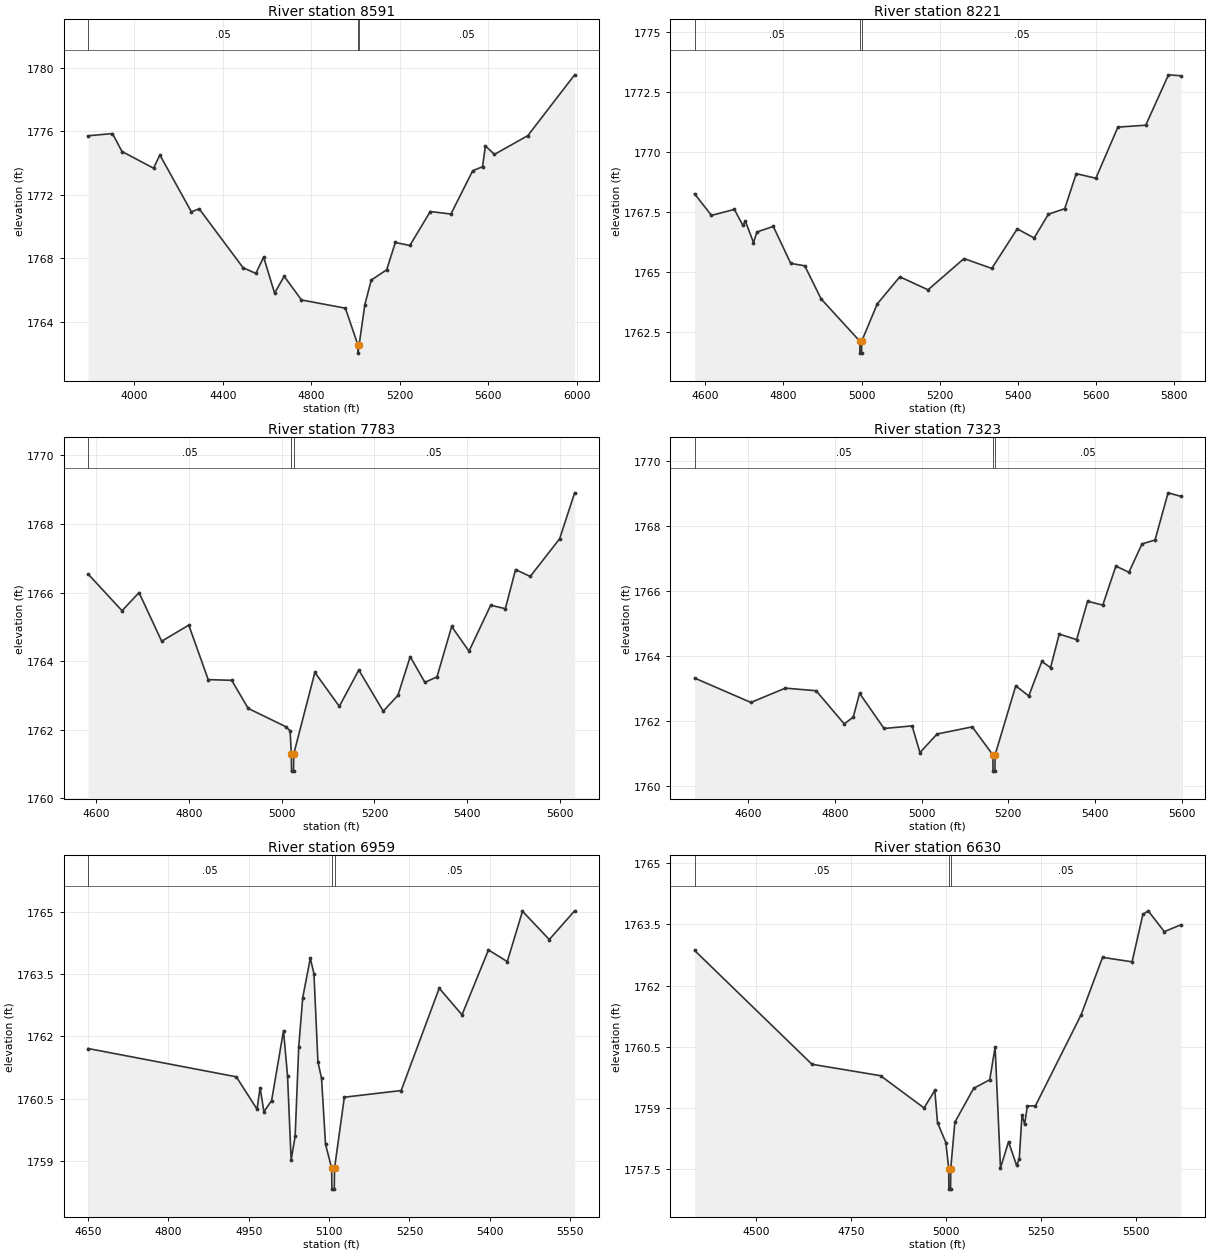
Type RM Length L Ch R = 1,8591,370,370,370
BEGIN DESCRIPTION:
Deadman 58 4.0
END DESCRIPTION:
XS GIS Cut Line= 3
      1622642.61      6864295.34      1623405.00      6865238.00
      1624305.04      6865638.02
#Sta/Elev= 30
  3792.2 1775.71  3902.1 1775.85  3945.3 1774.72  4087.6 1773.67  4116.4 1774.50
  4258.6 1770.92  4293.8 1771.11  4492.1 1767.40  4549.7 1767.04  4584.9 1768.07
  4634.4 1765.80  4677.6 1766.86  4755.9 1765.37  4954.2 1764.85  5011.0 1762.52
  5011.4 1762.02  5016.0 1762.52  5042.2 1765.08  5070.9 1766.62  5140.7 1767.27
  5179.7 1768.99  5245.3 1768.80  5337.6 1770.94  5430.7 1770.78  5529.2 1773.51
  5573.6 1773.76  5586.6 1775.07  5627.6 1774.54  5778.1 1775.72  5989.5 1779.55
#Mann=3,-1,0
  3792.2    0.05       0  5011.0    0.03       0  5016.0    0.05       0
Bank Sta=5011,5016
Exp/Cntr=0.3,0.1

Type RM Length L Ch R = 1,8221,438,438,438
BEGIN DESCRIPTION:
Mapping XS 052578d1
END DESCRIPTION:
XS GIS Cut Line= 3
      1622807.84      6864943.89      1623059.82      6865311.53
      1623711.26      6865777.44
#Sta/Elev= 30
  4572.2 1768.26  4615.5 1767.36  4674.2 1767.61  4696.1 1766.94  4702.2 1767.13
  4723.1 1766.23  4732.0 1766.67  4773.9 1766.90  4818.6 1765.36  4854.5 1765.26
  4896.4 1763.88  4995.5 1762.12  4995.8 1761.62  5000.1 1761.62  5000.5 1762.12
  5040.2 1763.67  5098.0 1764.80  5170.4 1764.26  5262.5 1765.56  5333.8 1765.15
  5398.9 1766.80  5442.3 1766.42  5478.8 1767.41  5520.6 1767.64  5550.1 1769.10
  5600.4 1768.91  5656.9 1771.04  5728.2 1771.12  5786.5 1773.22  5818.8 1773.18
#Mann=3,-1,0
  4572.2    0.05       0  4995.5    0.05       0  5000.5    0.05       0
Bank Sta=4995.5,5000.5
Exp/Cntr=0.3,0.1

Type RM Length L Ch R = 1,7783,460,460,460
BEGIN DESCRIPTION:
Mapping XS 5f7b1e2a
END DESCRIPTION:
XS GIS Cut Line= 3
      1622464.97      6865406.55      1622807.83      6865646.14
      1623406.78      6865844.42
#Sta/Elev= 30
  4582.5 1766.54  4655.7 1765.47  4692.3 1766.00  4741.1 1764.58  4799.6 1765.05
  4841.5 1763.46  4892.1 1763.44  4927.8 1762.62  5008.3 1762.09  5018.1 1761.97
  5020.8 1761.29  5021.2 1760.79  5025.5 1760.79  5025.9 1761.29  5071.5 1763.67
  5124.2 1762.68  5166.3 1763.74  5219.0 1762.54  5250.6 1763.00  5277.1 1764.13
  5308.8 1763.38  5334.9 1763.54  5366.5 1765.01  5403.9 1764.29  5450.7 1765.63
  5482.3 1765.53  5504.3 1766.67  5536.0 1766.47  5599.4 1767.57  5631.7 1768.91
#Mann=3,-1,0
  4582.5    0.05       0  5020.8    0.05       0  5025.9    0.05       0
Bank Sta=5020.8,5025.9
Exp/Cntr=0.3,0.1

Type RM Length L Ch R = 1,7323,364,364,364
BEGIN DESCRIPTION:
Mapping XS 764366c7
END DESCRIPTION:
XS GIS Cut Line= 3
      1622324.49      6865786.58      1622733.47      6866088.15
      1623344.87      6866141.86
#Sta/Elev= 30
  4476.5 1763.32  4606.4 1762.57  4685.8 1763.01  4756.8 1762.93  4821.6 1761.91
  4842.4 1762.12  4857.0 1762.85  4913.4 1761.77  4978.1 1761.85  4996.2 1761.03
  5035.7 1761.60  5116.7 1761.82  5164.3 1760.96  5164.7 1760.46  5169.1 1760.46
  5169.5 1760.96  5217.1 1763.08  5247.2 1762.77  5277.3 1763.83  5297.4 1763.64
  5317.4 1764.67  5357.6 1764.50  5382.8 1765.68  5417.8 1765.56  5448.0 1766.76
  5478.1 1766.57  5508.2 1767.44  5538.3 1767.56  5568.4 1769.01  5598.4 1768.90
#Mann=3,-1,0
  4476.5    0.05       0  5164.3    0.05       0  5169.5    0.05       0
Bank Sta=5164.3,5169.5
Exp/Cntr=0.3,0.1

Type RM Length L Ch R = 1,6959,329,329,329
BEGIN DESCRIPTION:
Mapping XS af90e8d4
END DESCRIPTION:
XS GIS Cut Line= 3
      1622374.06      6866026.16      1622531.05      6866331.88
      1622948.25      6866711.90
#Sta/Elev= 30
  4650.3 1761.71  4926.9 1761.03  4965.6 1760.25  4971.3 1760.77  4978.4 1760.19
  4992.8 1760.46  5015.0 1762.14  5022.5 1761.05  5029.2 1759.03  5036.7 1759.60
  5043.4 1761.75  5050.8 1762.93  5065.0 1763.88  5071.8 1763.51  5079.2 1761.39
  5086.0 1760.99  5093.4 1759.41  5104.9 1758.83  5105.3 1758.33  5109.7 1758.33
  5110.2 1758.83  5128.5 1760.54  5234.6 1760.70  5305.6 1763.16  5348.1 1762.52
  5397.5 1764.08  5432.6 1763.80  5461.0 1765.01  5511.0 1764.33  5558.3 1765.02
#Mann=3,-1,0
  4650.3    0.05       0  5104.9    0.05       0  5110.2    0.05       0
Bank Sta=5104.9,5110.2
Exp/Cntr=0.3,0.1

Type RM Length L Ch R = 1,6630,562,562,562
BEGIN DESCRIPTION:
Mapping XS dfcd09c5
END DESCRIPTION:
XS GIS Cut Line= 3
      1621994.85      6865887.62      1622279.06      6866501.25
      1622704.54      6866930.86
#Sta/Elev= 30
  4337.8 1762.86  4646.8 1760.07  4827.3 1759.79  4941.9 1759.00  4970.3 1759.43
  4977.4 1758.64  4999.4 1758.15  5006.9 1757.51  5007.3 1757.01  5011.8 1757.01
  5012.2 1757.51  5023.1 1758.65  5072.5 1759.48  5114.9 1759.69  5129.1 1760.49
  5143.2 1757.53  5164.4 1758.17  5185.7 1757.59  5192.7 1757.76  5199.8 1758.83
  5206.8 1758.60  5213.9 1759.05  5235.1 1759.05  5355.4 1761.28  5411.9 1762.69
  5489.7 1762.58  5518.0 1763.74  5532.1 1763.83  5574.5 1763.32  5618.7 1763.49
#Mann=3,-1,0
  4337.8    0.05       0  5006.9    0.05       0  5012.2    0.05       0
Bank Sta=5006.9,5012.2
Exp/Cntr=0.3,0.1

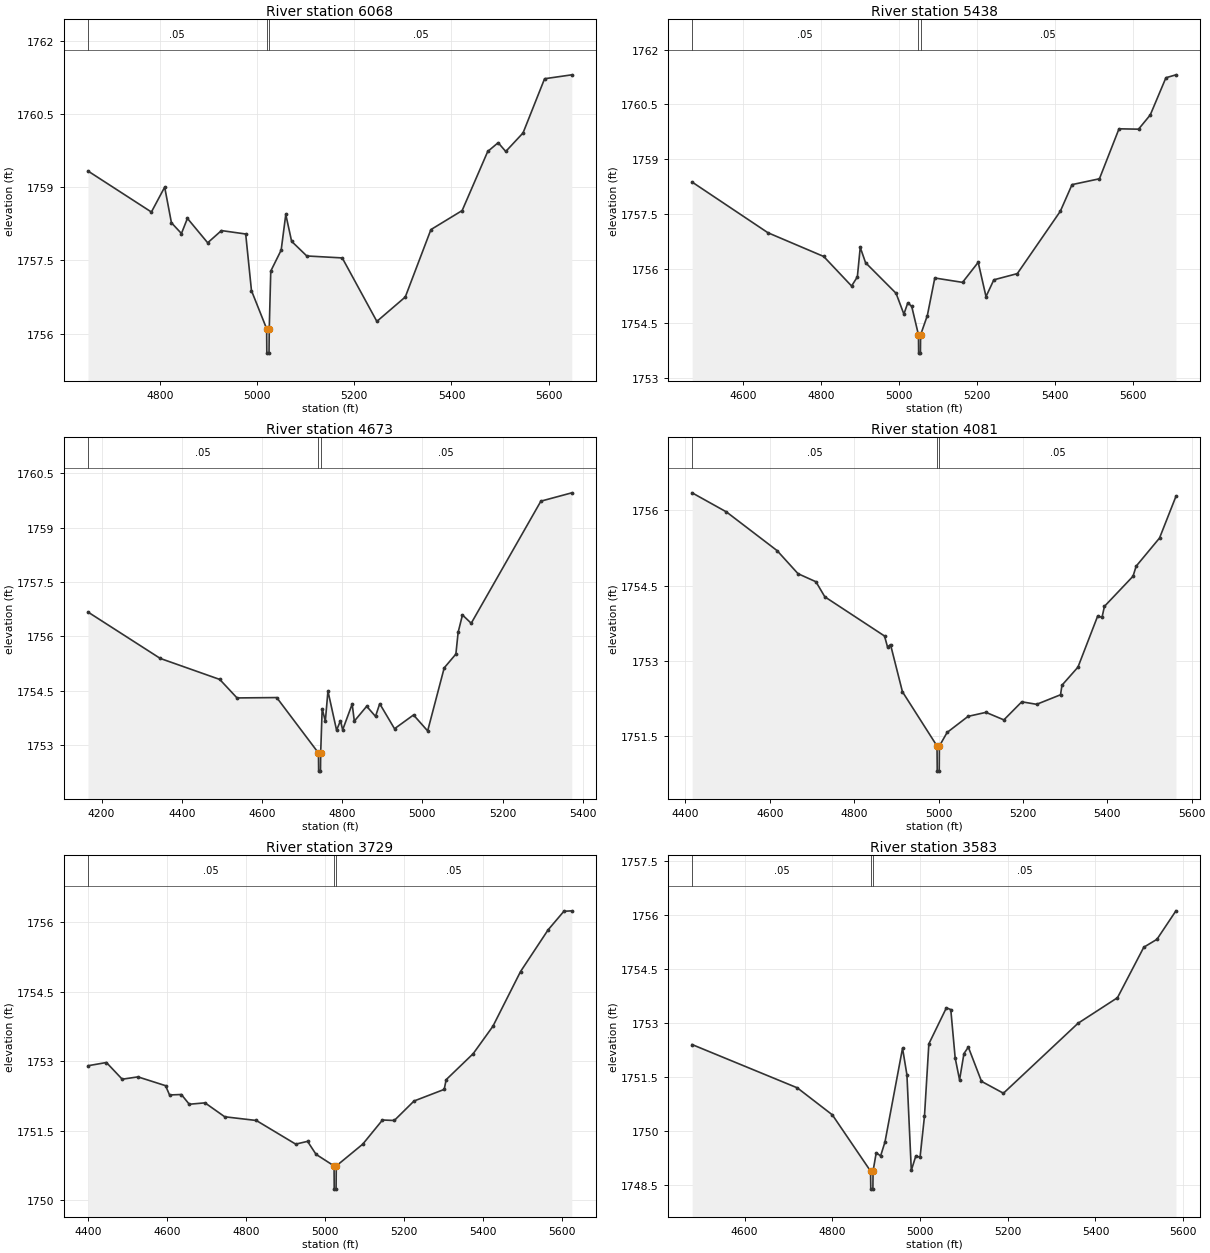
Type RM Length L Ch R = 1,6068,630,630,630
BEGIN DESCRIPTION:
Mapping XS c86e36e9
END DESCRIPTION:
XS GIS Cut Line= 3
      1621812.25      6866311.19      1621894.88      6866649.97
      1622451.31      6866979.70
#Sta/Elev= 30
  4652.1 1759.33  4782.6 1758.49  4809.9 1759.00  4823.8 1758.27  4844.4 1758.05
  4856.7 1758.36  4898.4 1757.86  4926.7 1758.11  4976.6 1758.04  4988.5 1756.88
  5019.7 1756.10  5020.1 1755.60  5024.6 1755.60  5025.1 1756.10  5028.2 1757.28
  5049.6 1757.71  5059.1 1758.44  5071.1 1757.89  5102.3 1757.59  5175.3 1757.55
  5246.5 1756.25  5305.0 1756.75  5357.7 1758.13  5422.0 1758.52  5474.6 1759.73
  5496.1 1759.91  5511.7 1759.73  5547.3 1760.11  5591.6 1761.22  5647.6 1761.30
#Mann=3,-1,0
  4652.1    0.05       0  5019.7    0.05       0  5025.1    0.05       0
Bank Sta=5019.7,5025.1
Exp/Cntr=0.3,0.1

Type RM Length L Ch R = 1,5438,765,765,765
BEGIN DESCRIPTION:
Mapping XS b9b14c70
END DESCRIPTION:
XS GIS Cut Line= 3
      1621262.84      6866839.99      1621667.68      6867125.03
      1622410.67      6867170.43
#Sta/Elev= 30
  4470.1 1758.37  4664.4 1756.98  4807.2 1756.33  4878.6 1755.52  4893.4 1755.77
  4900.8 1756.58  4914.4 1756.16  4992.6 1755.32  5012.6 1754.75  5022.7 1755.06
  5032.7 1754.96  5050.0 1754.18  5050.4 1753.68  5055.0 1753.68  5055.4 1754.18
  5072.7 1754.71  5091.8 1755.74  5162.9 1755.62  5203.0 1756.17  5223.0 1755.23
  5243.1 1755.69  5303.2 1755.86  5413.4 1757.57  5443.4 1758.30  5513.6 1758.46
  5563.7 1759.83  5613.8 1759.82  5643.8 1760.21  5683.9 1761.23  5709.6 1761.31
#Mann=3,-1,0
  4470.1    0.05       0  5050.0    0.05       0  5055.4    0.05       0
Bank Sta=5050,5055.4
Exp/Cntr=0.3,0.1

Type RM Length L Ch R = 1,4673,592,592,592
BEGIN DESCRIPTION:
Mapping XS baa8b02b
END DESCRIPTION:
XS GIS Cut Line= 3
      1621241.61      6867148.40      1621639.14      6867628.54
      1622176.02      6867855.68
#Sta/Elev= 30
  4166.2 1756.67  4346.4 1755.39  4494.8 1754.81  4537.8 1754.30  4636.8 1754.31
  4740.9 1752.78  4741.3 1752.28  4745.9 1752.28  4746.4 1752.78  4750.1 1754.00
  4758.0 1753.66  4764.5 1754.49  4786.0 1753.41  4795.7 1753.67  4801.2 1753.42
  4824.9 1754.13  4830.3 1753.66  4861.1 1754.07  4883.1 1753.79  4893.6 1754.14
  4930.5 1753.45  4977.9 1753.83  5013.1 1753.39  5054.4 1755.13  5083.5 1755.51
  5089.1 1756.11  5099.9 1756.59  5121.7 1756.36  5295.4 1759.73  5372.5 1759.96
#Mann=3,-1,0
  4166.2    0.05       0  4740.9    0.05       0  4746.4    0.05       0
Bank Sta=4740.9,4746.4
Exp/Cntr=0.3,0.1

Type RM Length L Ch R = 1,4081,352,352,352
BEGIN DESCRIPTION:
Mapping XS b6b158fd
END DESCRIPTION:
XS GIS Cut Line= 3
      1620911.69      6867356.34      1621543.75      6867967.75
      1621808.16      6868009.06
#Sta/Elev= 30
  4415.8 1756.35  4497.1 1755.97  4617.2 1755.20  4666.9 1754.74  4709.3 1754.58
  4730.4 1754.28  4871.9 1753.50  4879.1 1753.28  4886.1 1753.33  4914.4 1752.39
  4996.4 1751.31  4996.9 1750.81  5001.6 1750.81  5002.0 1751.31  5020.3 1751.58
  5070.0 1751.90  5112.4 1751.98  5154.9 1751.83  5197.3 1752.19  5232.6 1752.14
  5289.2 1752.33  5292.6 1752.52  5330.5 1752.88  5377.4 1753.90  5387.5 1753.87
  5393.3 1754.09  5461.1 1754.69  5468.5 1754.89  5523.9 1755.45  5562.8 1756.28
#Mann=3,-1,0
  4415.8    0.05       0  4996.4   0.035       0  5002.0    0.05       0
Bank Sta=4996.4,5002
Exp/Cntr=0.3,0.1

Type RM Length L Ch R = 1,3729,146,146,146
BEGIN DESCRIPTION:
Mapping XS c397803a
END DESCRIPTION:
XS GIS Cut Line= 2
      1620548.22      6868025.58      1621775.06      6868062.76
#Sta/Elev= 30
  4398.7 1752.90  4445.5 1752.97  4485.5 1752.61  4525.5 1752.66  4595.6 1752.47
  4605.6 1752.27  4635.6 1752.28  4655.6 1752.07  4695.6 1752.10  4745.6 1751.80
  4825.7 1751.72  4925.7 1751.21  4955.7 1751.27  4977.3 1750.99  5023.0 1750.74
  5023.4 1750.24  5028.1 1750.24  5028.6 1750.74  5095.8 1751.21  5145.8 1751.73
  5175.8 1751.72  5225.9 1752.14  5302.4 1752.39  5307.4 1752.60  5375.9 1753.16
  5425.9 1753.75  5496.0 1754.93  5566.0 1755.83  5606.0 1756.23  5626.1 1756.24
#Mann=3,-1,0
  4398.7    0.05       0  5023.0   0.035       0  5028.6    0.05       0
Bank Sta=5023,5028.6
Exp/Cntr=0.3,0.1

Type RM Length L Ch R = 1,3583,354,354,354
BEGIN DESCRIPTION:
Mapping XS c0fbb77f
END DESCRIPTION:
XS GIS Cut Line= 2
      1620585.35      6868170.16      1621688.31      6868178.43
#Sta/Elev= 30
  4480.4 1752.40  4720.1 1751.20  4800.1 1750.45  4887.2 1748.89  4887.7 1748.39
  4892.5 1748.39  4892.9 1748.89  4900.1 1749.40  4910.1 1749.31  4920.1 1749.70
  4960.1 1752.30  4970.1 1751.56  4980.1 1748.91  4990.1 1749.30  5000.1 1749.28
  5010.1 1750.41  5020.1 1752.42  5060.1 1753.42  5070.1 1753.37  5080.1 1752.03
  5090.1 1751.42  5100.1 1752.15  5110.1 1752.33  5140.1 1751.38  5190.1 1751.05
  5360.1 1752.99  5450.1 1753.70  5510.1 1755.10  5540.1 1755.32  5583.4 1756.11
#Mann=3,-1,0
  4480.4    0.05       0  4887.2    0.05       0  4892.9    0.05       0
Bank Sta=4887.2,4892.9
Exp/Cntr=0.3,0.1

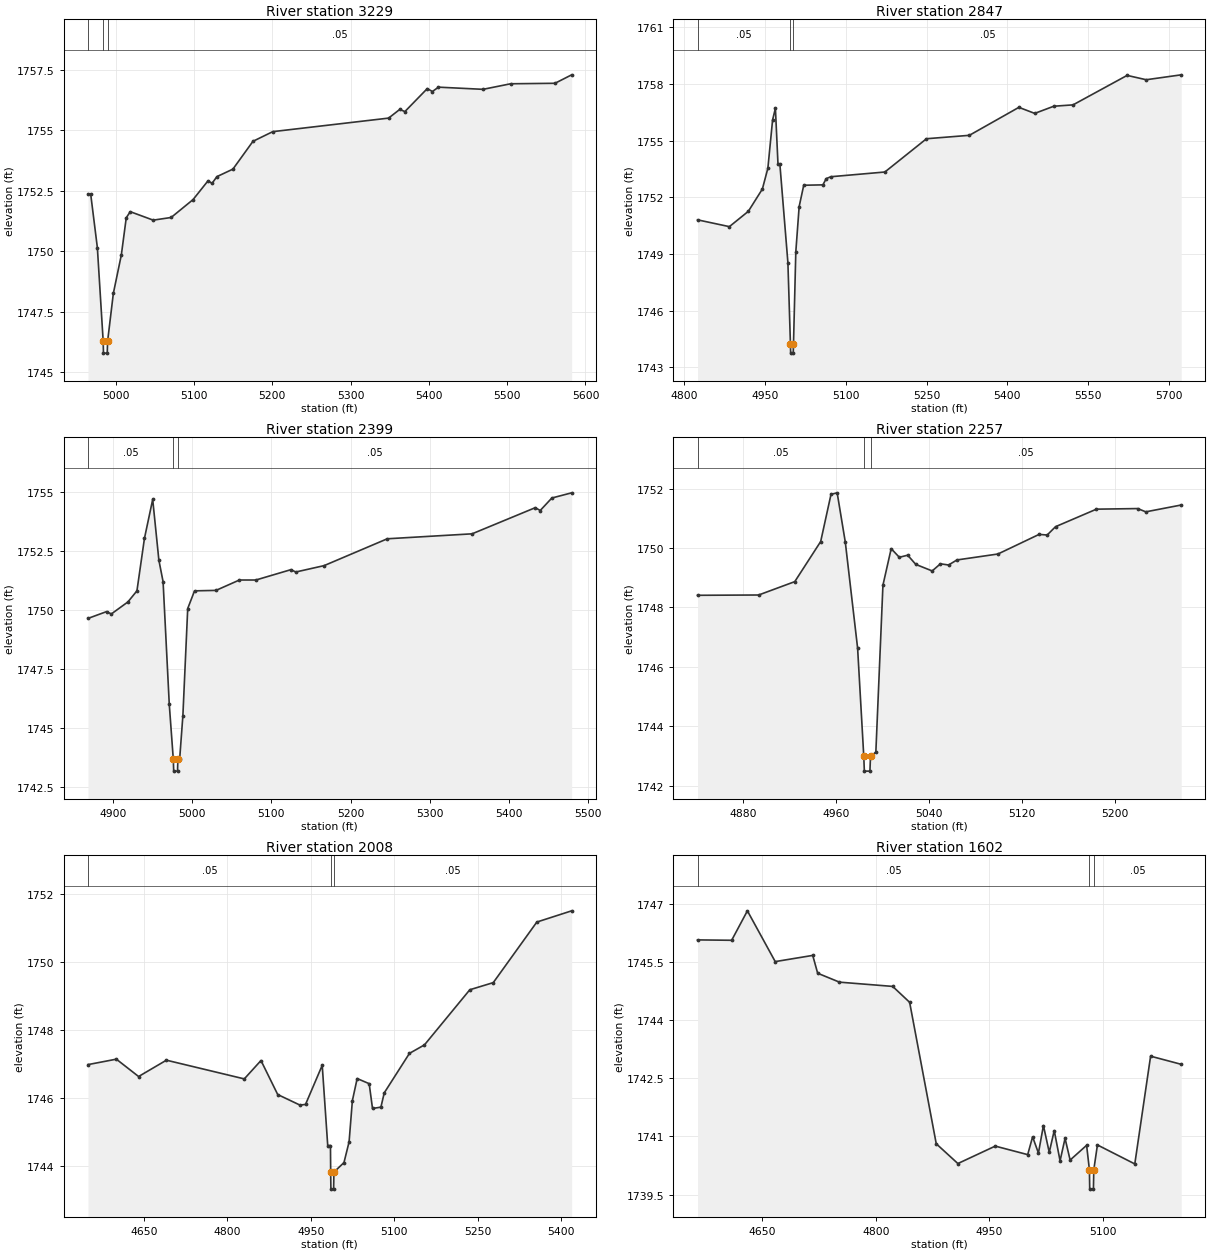
Type RM Length L Ch R = 1,3229,382,382,382
BEGIN DESCRIPTION:
Mapping XS 50db7662
END DESCRIPTION:
XS GIS Cut Line= 3
      1621223.17      6868482.35      1621568.23      6868416.80
      1621771.19      6868244.13
#Sta/Elev= 30
  4964.7 1752.36  4968.2 1752.36  4976.7 1750.15  4984.1 1746.29  4984.5 1745.79
  4989.3 1745.79  4989.8 1746.29  4997.1 1748.26  5007.3 1749.85  5013.6 1751.39
  5018.7 1751.64  5048.0 1751.29  5070.9 1751.40  5098.9 1752.14  5118.1 1752.92
  5123.1 1752.81  5129.4 1753.09  5149.8 1753.40  5175.4 1754.55  5200.7 1754.95
  5348.6 1755.51  5362.9 1755.87  5369.4 1755.78  5398.0 1756.73  5404.6 1756.61
  5412.3 1756.79  5469.2 1756.70  5504.5 1756.93  5561.1 1756.95  5582.4 1757.30
#Mann=3,-1,0
  4964.7    0.05       0  4984.1    0.05       0  4989.8    0.05       0
Bank Sta=4984.1,4989.8
Exp/Cntr=0.3,0.1

Type RM Length L Ch R = 1,2847,448,448,448
BEGIN DESCRIPTION:
Mapping XS 3a10f022
END DESCRIPTION:
XS GIS Cut Line= 3
      1621257.14      6868852.02      1621406.84      6868821.05
      1622009.92      6868382.91
#Sta/Elev= 30
  4824.5 1750.81  4883.6 1750.45  4918.8 1751.26  4944.9 1752.44  4955.1 1753.54
  4963.9 1756.10  4969.1 1756.71  4973.9 1753.75  4977.4 1753.75  4992.3 1748.55
  4997.0 1744.26  4997.4 1743.76  5002.2 1743.76  5002.7 1744.26  5007.0 1749.12
  5013.2 1751.51  5021.7 1752.64  5057.3 1752.66  5063.5 1752.99  5072.0 1753.09
  5172.4 1753.34  5249.7 1755.10  5329.3 1755.28  5421.3 1756.76  5450.7 1756.44
  5486.2 1756.82  5521.8 1756.89  5622.3 1758.45  5657.8 1758.22  5722.8 1758.48
#Mann=3,-1,0
  4824.5    0.05       0  4997.0    0.05       0  5002.7    0.05       0
Bank Sta=4997,5002.7
Exp/Cntr=0.3,0.1

Type RM Length L Ch R = 1,2399,142,142,142
BEGIN DESCRIPTION:
Mapping XS 2821c550
END DESCRIPTION:
XS GIS Cut Line= 3
      1621526.77      6869229.59      1621635.27      6869196.89
      1621924.25      6868792.31
#Sta/Elev= 30
  4868.5 1749.65  4892.0 1749.94  4898.0 1749.84  4918.9 1750.35  4930.3 1750.82
  4939.8 1753.05  4950.2 1754.70  4958.0 1752.12  4963.3 1751.21  4971.1 1746.01
  4976.2 1743.67  4976.7 1743.17  4981.5 1743.17  4982.0 1743.67  4984.2 1743.67
  4988.3 1745.53  4994.4 1750.07  5003.0 1750.82  5030.1 1750.84  5059.6 1751.28
  5080.4 1751.28  5124.7 1751.72  5130.8 1751.62  5166.5 1751.89  5246.3 1753.03
  5353.3 1753.24  5433.1 1754.35  5439.3 1754.23  5454.0 1754.76  5479.0 1754.98
#Mann=3,-1,0
  4868.5    0.05       0  4976.2    0.05       0  4982.0    0.05       0
Bank Sta=4976.2,4982
Exp/Cntr=0.3,0.1

Type RM Length L Ch R = 1,2257,249,249,249
BEGIN DESCRIPTION:
Mapping XS 50b69c9b
END DESCRIPTION:
XS GIS Cut Line= 3
      1621554.81      6869361.75      1621699.84      6869311.55
      1621883.89      6869123.78
#Sta/Elev= 30
  4840.9 1748.41  4893.5 1748.42  4924.6 1748.87  4946.9 1750.22  4955.8 1751.81
  4961.1 1751.86  4968.1 1750.20  4978.7 1746.63  4984.0 1742.99  4984.5 1742.49
  4989.3 1742.49  4989.8 1742.99  4994.4 1743.13  5000.5 1748.75  5007.6 1749.98
  5014.6 1749.69  5021.8 1749.76  5028.8 1749.45  5042.9 1749.23  5050.0 1749.47
  5057.0 1749.43  5064.2 1749.60  5099.5 1749.80  5134.9 1750.46  5141.9 1750.44
  5149.1 1750.72  5184.3 1751.31  5219.8 1751.33  5226.8 1751.22  5257.3 1751.45
#Mann=3,-1,0
  4840.9    0.05       0  4984.0    0.05       0  4989.8    0.05       0
Bank Sta=4984,4989.8
Exp/Cntr=0.3,0.1

Type RM Length L Ch R = 1,2008,406,406,406
BEGIN DESCRIPTION:
Mapping XS 11fed203
END DESCRIPTION:
XS GIS Cut Line= 3
      1621364.02      6869529.04      1621799.82      6869538.18
      1622037.52      6869175.53
#Sta/Elev= 30
  4549.4 1746.99  4600.4 1747.15  4640.4 1746.64  4690.4 1747.12  4830.4 1746.57
  4860.4 1747.11  4890.5 1746.11  4930.5 1745.80  4940.5 1745.82  4970.5 1746.97
  4980.4 1744.61  4985.3 1744.61  4985.7 1743.83  4986.1 1743.33  4991.0 1743.33
  4991.5 1743.83  5009.6 1744.11  5018.8 1744.72  5024.7 1745.93  5033.3 1746.58
  5054.9 1746.43  5060.9 1745.70  5076.0 1745.74  5082.0 1746.16  5127.3 1747.32
  5154.3 1747.57  5235.8 1749.19  5278.0 1749.40  5356.3 1751.18  5418.9 1751.51
#Mann=3,-1,0
  4549.4    0.05       0  4985.7    0.05       0  4991.5    0.05       0
Bank Sta=4985.7,4991.5
Exp/Cntr=0.3,0.1

Type RM Length L Ch R = 1,1602,94,94,94
BEGIN DESCRIPTION:
Mapping XS 14812f47
END DESCRIPTION:
XS GIS Cut Line= 3
      1621613.64      6869605.75      1621864.25      6869806.24
      1622106.82      6870012.73
#Sta/Elev= 30
  4564.2 1746.07  4609.3 1746.06  4630.1 1746.82  4666.9 1745.51  4716.5 1745.67
  4723.0 1745.21  4751.8 1744.98  4822.2 1744.87  4844.6 1744.46  4879.8 1740.81
  4908.4 1740.30  4957.8 1740.75  5000.7 1740.53  5007.2 1740.99  5014.9 1740.57
  5021.5 1741.28  5029.2 1740.59  5035.8 1741.15  5043.5 1740.37  5050.1 1740.95
  5056.8 1740.39  5078.6 1740.77  5082.3 1740.14  5082.7 1739.64  5087.6 1739.64
  5088.1 1740.14  5092.9 1740.78  5142.3 1740.29  5163.2 1743.07  5203.7 1742.86
#Mann=3,-1,0
  4564.2    0.05       0  5082.3    0.05       0  5088.1    0.05       0
Bank Sta=5082.3,5088.1
Exp/Cntr=0.3,0.1

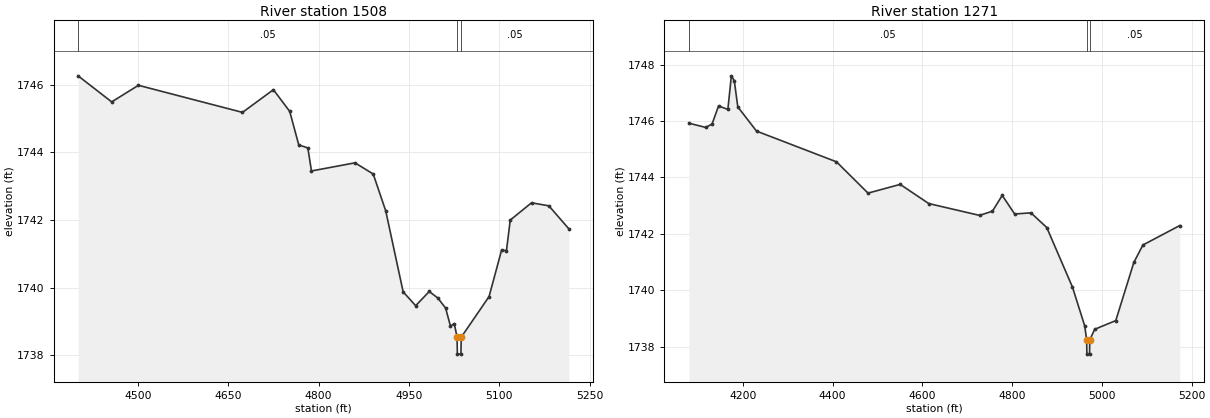
Type RM Length L Ch R = 1,1508,237,237,237
BEGIN DESCRIPTION:
Mapping XS 42c4d7e5
END DESCRIPTION:
XS GIS Cut Line= 3
      1621411.17      6869623.82      1621824.15      6869894.46
      1622075.54      6870093.97
#Sta/Elev= 30
  4400.8 1746.26  4456.6 1745.49  4501.0 1745.98  4673.7 1745.18  4725.0 1745.85
  4752.1 1745.21  4767.1 1744.22  4782.2 1744.13  4788.2 1743.45  4860.5 1743.69
  4890.7 1743.36  4911.5 1742.27  4940.4 1739.88  4961.2 1739.47  4983.7 1739.89
  4997.8 1739.70  5010.9 1739.40  5018.9 1738.87  5025.3 1738.94  5029.9 1738.54
  5030.4 1738.04  5036.3 1738.04  5036.8 1738.54  5083.0 1739.74  5103.8 1741.11
  5111.9 1741.10  5118.2 1742.00  5153.5 1742.51  5182.3 1742.42  5215.5 1741.74
#Mann=3,-1,0
  4400.8    0.05       0  5029.9    0.05       0  5036.8    0.05       0
Bank Sta=5029.9,5036.8
Exp/Cntr=0.3,0.1

Type RM Length L Ch R = 1,1271,0,0,0
BEGIN DESCRIPTION:
Deadman 58 1.0
END DESCRIPTION:
XS GIS Cut Line= 3
      1621149.59      6869590.66      1621858.90      6870183.90
      1622026.60      6870164.55
#Sta/Elev= 30
  4079.9 1745.92  4117.1 1745.77  4131.4 1745.89  4145.8 1746.53  4166.6 1746.41
  4174.4 1747.60  4180.9 1747.43  4188.7 1746.50  4230.4 1745.64  4408.6 1744.55
  4478.9 1743.44  4550.5 1743.75  4614.2 1743.07  4727.4 1742.65  4756.1 1742.80
  4777.9 1743.36  4805.5 1742.70  4841.9 1742.74  4877.1 1742.22  4934.3 1740.11
  4961.7 1738.73  4966.0 1738.23  4966.5 1737.73  4972.4 1737.73  4972.9 1738.23
  4983.8 1738.61  5030.9 1738.92  5071.1 1740.98  5091.3 1741.60  5173.4 1742.29
#Mann=3,-1,0
  4079.9    0.05       0  4966.0    0.05       0  4972.9    0.05       0
Bank Sta=4966,4972.9
Exp/Cntr=0.3,0.1

Chan Stop Cuts=-1