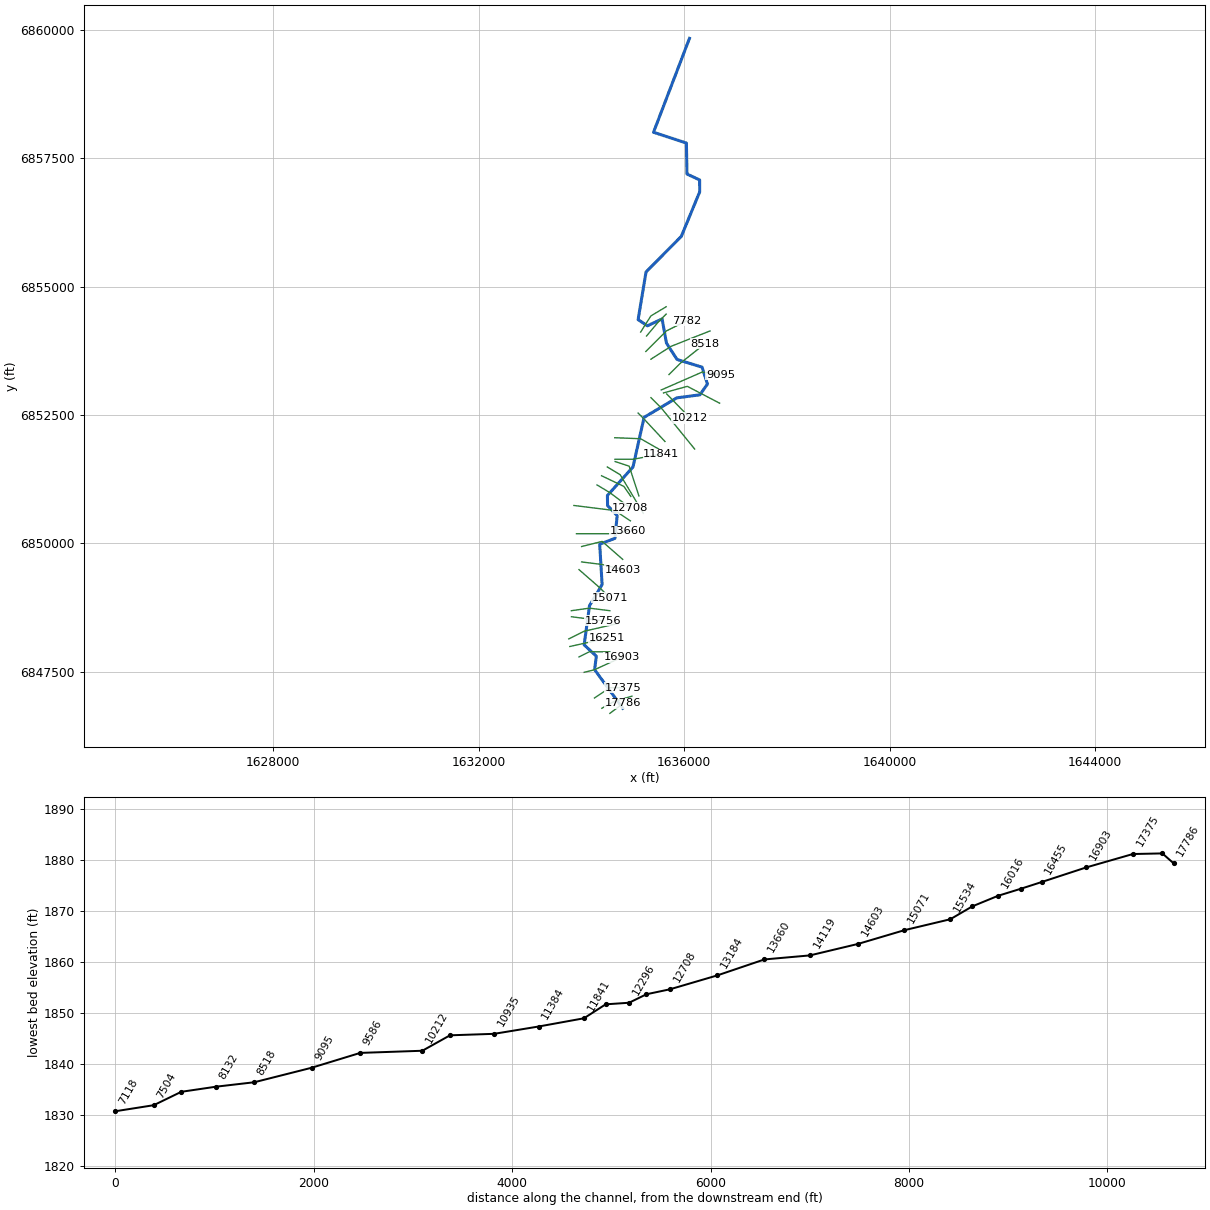
--- Deadman 59.prj (project) ---

Proj Title=Deadman 59 Base Level Engineering
Current Plan=p01
Default Exp/Contr=0.3,0.1
English Units
Geom File=g01
Flow File=f01
Plan File=p01
Y Axis Title=Elevation
X Axis Title(PF)=Main Channel Distance
X Axis Title(XS)=Station
BEGIN DESCRIPTION:
Deadman 59
END DESCRIPTION:
DSS Export Rating Curves= 0
DSS Export Rating Curve Sorted= 0
DSS Export Volume Flow Curves= 0
DXF OffsetX= 0
DXF OffsetY= 0
DXF ScaleX= 1
DXF ScaleY= 10

--- Deadman 59.p01 (plan) ---

Plan Title=Multiple Run
Short Identifier=Multiple
Geom File=g01
Flow File=f01
Subcritical Flow
K Sum by GR= 0
Std Step Tol= 0.01
Critical Tol= 0.01
Num of Std Step Trials= 20
Max Error Tol= 0.3
Flow Tol Ratio= 0.001
Split Flow NTrial= 30
Split Flow Tol= 0.02
Split Flow Ratio= 0.02
Log Output Level= 0
Friction Slope Method= 1
Unsteady Friction Slope Method= 2
Unsteady Bridges Friction Slope Method= 1
Parabolic Critical Depth
Global Vel Dist=  1 , 1 , 1
Global Log Level= 0
CheckData=True
Encroach Param= -1, 0, 0, 0
BEGIN DESCRIPTION:
Multiple Run
END DESCRIPTION:

--- Deadman 59.f01 (steady flow) ---

Flow Title=Multiple
Number of Profiles=7
Profile Names=10-year,25-year,50-year,1pct_min,100-year,1pct_plu,500-year
River Rch & RM= Deadman 59,Reach-1,17786
     176     237     287     173     344     687     503
River Rch & RM= Deadman 59,Reach-1,17672
     237     326     399     243     485     967     726
River Rch & RM= Deadman 59,Reach-1,11841
     474     672     839     520    1038    2072    1611
River Rch & RM= Deadman 59,Reach-1,2064
     509     728     913     569    1136    2266    1781
Boundary for River Rch & Prof#=Deadman 59,Reach-1,1
Up Type=0
Dn Type=3
Dn Slope=0.007
Boundary for River Rch & Prof#=Deadman 59,Reach-1,2
Up Type=0
Dn Type=3
Dn Slope=0.007
Boundary for River Rch & Prof#=Deadman 59,Reach-1,3
Up Type=0
Dn Type=3
Dn Slope=0.007
Boundary for River Rch & Prof#=Deadman 59,Reach-1,4
Up Type=0
Dn Type=3
Dn Slope=0.007
Boundary for River Rch & Prof#=Deadman 59,Reach-1,5
Up Type=0
Dn Type=3
Dn Slope=0.007
Boundary for River Rch & Prof#=Deadman 59,Reach-1,6
Up Type=0
Dn Type=3
Dn Slope=0.007
Boundary for River Rch & Prof#=Deadman 59,Reach-1,7
Up Type=0
Dn Type=3
Dn Slope=0.007

--- Deadman 59.g01 (geometry) ---

Geom Title=Existing Conditions

River Reach=Deadman 59,Reach-1
Reach XY= 30
      1634805.00      6846788.00      1634258.13      6847539.63
      1634291.78      6847801.67      1634054.51      6848022.80
      1634158.76      6848786.44      1634403.95      6849198.44
      1634357.06      6849982.17      1634653.81      6850098.47
      1634696.92      6850541.31      1634510.35      6850735.27
      1634507.24      6850932.07      1635005.00      6851488.00
      1635221.46      6852455.13      1635856.58      6852834.33
      1636307.44      6852893.52      1636454.63      6853103.27
      1636349.74      6853432.53      1635863.15      6853581.93
      1635656.92      6853899.95      1635571.79      6854371.61
      1635284.87      6854237.59      1635104.91      6854357.88
      1635258.74      6855286.47      1635946.84      6855981.95
      1636303.95      6856848.44      1636302.07      6857080.03
      1636056.54      6857193.85      1636044.64      6857798.16
      1635404.79      6858008.05      1636105.00      6859838.00

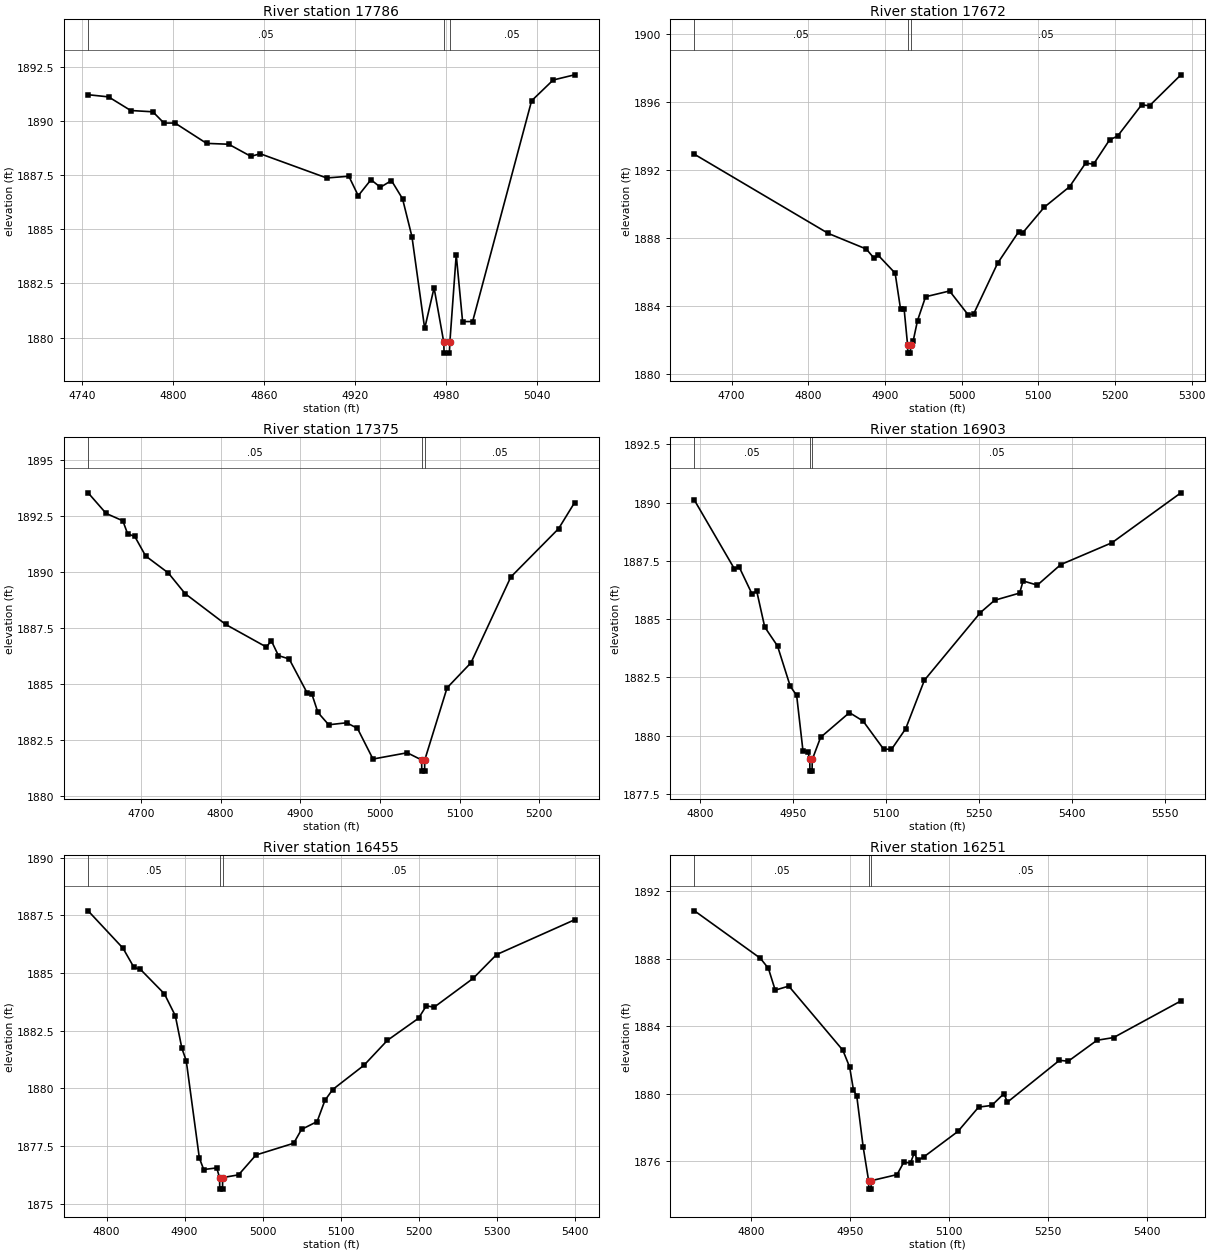
Type RM Length L Ch R = 1,17786,114,114,114
BEGIN DESCRIPTION:
Deadman 59 35.0
END DESCRIPTION:
XS GIS Cut Line= 3
      1634555.00      6846688.00      1634755.00      6846838.00
      1634804.99      6846887.99
#Sta/Elev= 30
  4743.8 1891.23  4757.3 1891.13  4771.9 1890.50  4786.5 1890.44  4793.8 1889.92
  4801.1 1889.92  4821.9 1888.98  4836.5 1888.94  4851.1 1888.38  4857.3 1888.50
  4901.1 1887.38  4915.7 1887.46  4921.9 1886.56  4930.3 1887.30  4936.5 1886.95
  4943.8 1887.26  4951.1 1886.42  4957.3 1884.67  4965.7 1880.42  4971.9 1882.30
  4978.3 1879.78  4978.5 1879.28  4982.0 1879.28  4982.3 1879.78  4986.5 1883.83
  4990.7 1880.74  4997.3 1880.74  5036.2 1890.95  5050.4 1891.91  5064.5 1892.15
#Mann=3,-1,0
  4743.8    0.05       0  4978.3    0.05       0  4982.3    0.05       0
Bank Sta=4978.3,4982.3
Exp/Cntr=0.3,0.1

Type RM Length L Ch R = 1,17672,297,297,297
BEGIN DESCRIPTION:
Mapping XS 3557ef7a
END DESCRIPTION:
XS GIS Cut Line= 3
      1634398.62      6846788.10      1634638.23      6846919.81
      1634984.16      6847022.95
#Sta/Elev= 30
  4651.6 1892.94  4826.1 1888.28  4875.7 1887.36  4885.8 1886.82  4891.5 1886.98
  4913.3 1885.94  4920.3 1883.84  4925.0 1883.84  4929.5 1881.73  4929.8 1881.23
  4933.3 1881.23  4933.5 1881.73  4936.8 1881.94  4942.5 1883.15  4953.0 1884.55
  4984.3 1884.89  5008.3 1883.50  5015.6 1883.53  5046.9 1886.52  5074.6 1888.39
  5079.8 1888.32  5107.7 1889.82  5140.8 1891.03  5161.7 1892.42  5172.1 1892.36
  5193.0 1893.79  5203.4 1894.01  5234.7 1895.85  5245.1 1895.80  5286.0 1897.62
#Mann=3,-1,0
  4651.6    0.05       0  4929.5    0.03       0  4933.5    0.05       0
Bank Sta=4929.5,4933.5
Exp/Cntr=0.3,0.1

Type RM Length L Ch R = 1,17375,472,472,472
BEGIN DESCRIPTION:
Deadman 59 34.0
END DESCRIPTION:
XS GIS Cut Line= 3
      1634254.96      6846987.97      1634555.00      6847188.00
      1634805.00      6847188.00
#Sta/Elev= 30
  4633.7 1893.54  4656.3 1892.62  4677.3 1892.29  4683.3 1891.71  4692.3 1891.59
  4705.9 1890.72  4734.4 1889.96  4755.4 1889.04  4806.5 1887.66  4857.6 1886.65
  4863.6 1886.94  4872.6 1886.27  4886.1 1886.12  4908.7 1884.60  4914.7 1884.54
  4922.2 1883.73  4935.7 1883.18  4958.2 1883.27  4971.8 1883.02  4991.3 1881.65
  5034.3 1881.93  5052.3 1881.61  5052.6 1881.11  5056.1 1881.11  5056.3 1881.61
  5084.3 1884.83  5114.3 1885.95  5164.3 1889.78  5224.3 1891.94  5244.3 1893.10
#Mann=3,-1,0
  4633.7    0.05       0  5052.3    0.03       0  5056.3    0.05       0
Bank Sta=5052.3,5056.3
Exp/Cntr=0.3,0.1

Type RM Length L Ch R = 1,16903,448,448,448
BEGIN DESCRIPTION:
Deadman 59 33.0
END DESCRIPTION:
XS GIS Cut Line= 3
      1634055.02      6847488.01      1634255.00      6847538.00
      1634781.33      6847779.21
#Sta/Elev= 30
  4790.3 1890.10  4854.7 1887.16  4862.4 1887.24  4883.0 1886.09  4890.8 1886.20
  4903.7 1884.66  4924.3 1883.85  4944.9 1882.12  4955.2 1881.73  4965.5 1879.33
  4973.2 1879.32  4976.4 1878.98  4976.6 1878.48  4980.1 1878.48  4980.4 1878.98
  4993.9 1879.93  5040.4 1880.99  5062.4 1880.63  5095.4 1879.43  5108.2 1879.41
  5131.2 1880.30  5161.4 1882.38  5251.7 1885.28  5274.7 1885.81  5315.2 1886.12
  5320.7 1886.64  5343.7 1886.46  5381.4 1887.34  5464.2 1888.28  5575.4 1890.42
#Mann=3,-1,0
  4790.3    0.05       0  4976.4    0.05       0  4980.4    0.05       0
Bank Sta=4976.4,4980.4
Exp/Cntr=0.3,0.1

Type RM Length L Ch R = 1,16455,204,204,204
BEGIN DESCRIPTION:
Deadman 59 32.0
END DESCRIPTION:
XS GIS Cut Line= 3
      1633954.99      6847787.99      1634155.00      6847888.00
      1634554.98      6847888.00
#Sta/Elev= 30
  4776.3 1887.70  4821.0 1886.08  4835.0 1885.25  4843.4 1885.16  4874.1 1884.10
  4888.1 1883.15  4896.5 1881.74  4902.1 1881.20  4918.9 1876.98  4924.5 1876.48
  4941.2 1876.55  4944.8 1876.13  4945.1 1875.63  4948.6 1875.63  4948.8 1876.13
  4969.2 1876.25  4991.5 1877.11  5039.9 1877.62  5049.9 1878.22  5069.9 1878.56
  5079.9 1879.48  5089.9 1879.95  5129.9 1881.00  5159.9 1882.08  5199.9 1883.04
  5209.9 1883.58  5219.9 1883.52  5269.9 1884.77  5299.9 1885.80  5399.9 1887.31
#Mann=3,-1,0
  4776.3    0.05       0  4944.8    0.03       0  4948.8    0.05       0
Bank Sta=4944.8,4948.8
Exp/Cntr=0.3,0.1

Type RM Length L Ch R = 1,16251,235,235,235
BEGIN DESCRIPTION:
Mapping XS 59dd8580
END DESCRIPTION:
XS GIS Cut Line= 2
      1633775.74      6847990.69      1634494.51      6848150.42
#Sta/Elev= 30
  4714.4 1890.84  4814.1 1888.03  4826.3 1887.43  4836.6 1886.14  4857.1 1886.38
  4939.0 1882.58  4949.3 1881.58  4955.0 1880.24  4960.1 1879.85  4969.7 1876.86
  4978.0 1874.85  4978.2 1874.35  4981.7 1874.35  4982.0 1874.85  5021.0 1875.21
  5031.2 1875.94  5041.4 1875.90  5047.1 1876.50  5052.3 1876.05  5061.9 1876.27
  5113.2 1877.77  5144.5 1879.21  5164.4 1879.31  5182.9 1880.01  5188.0 1879.50
  5266.8 1881.98  5280.2 1881.93  5323.7 1883.17  5348.8 1883.33  5450.7 1885.50
#Mann=3,-1,0
  4714.4    0.05       0  4978.0    0.03       0  4982.0    0.05       0
Bank Sta=4978,4982
Exp/Cntr=0.3,0.1

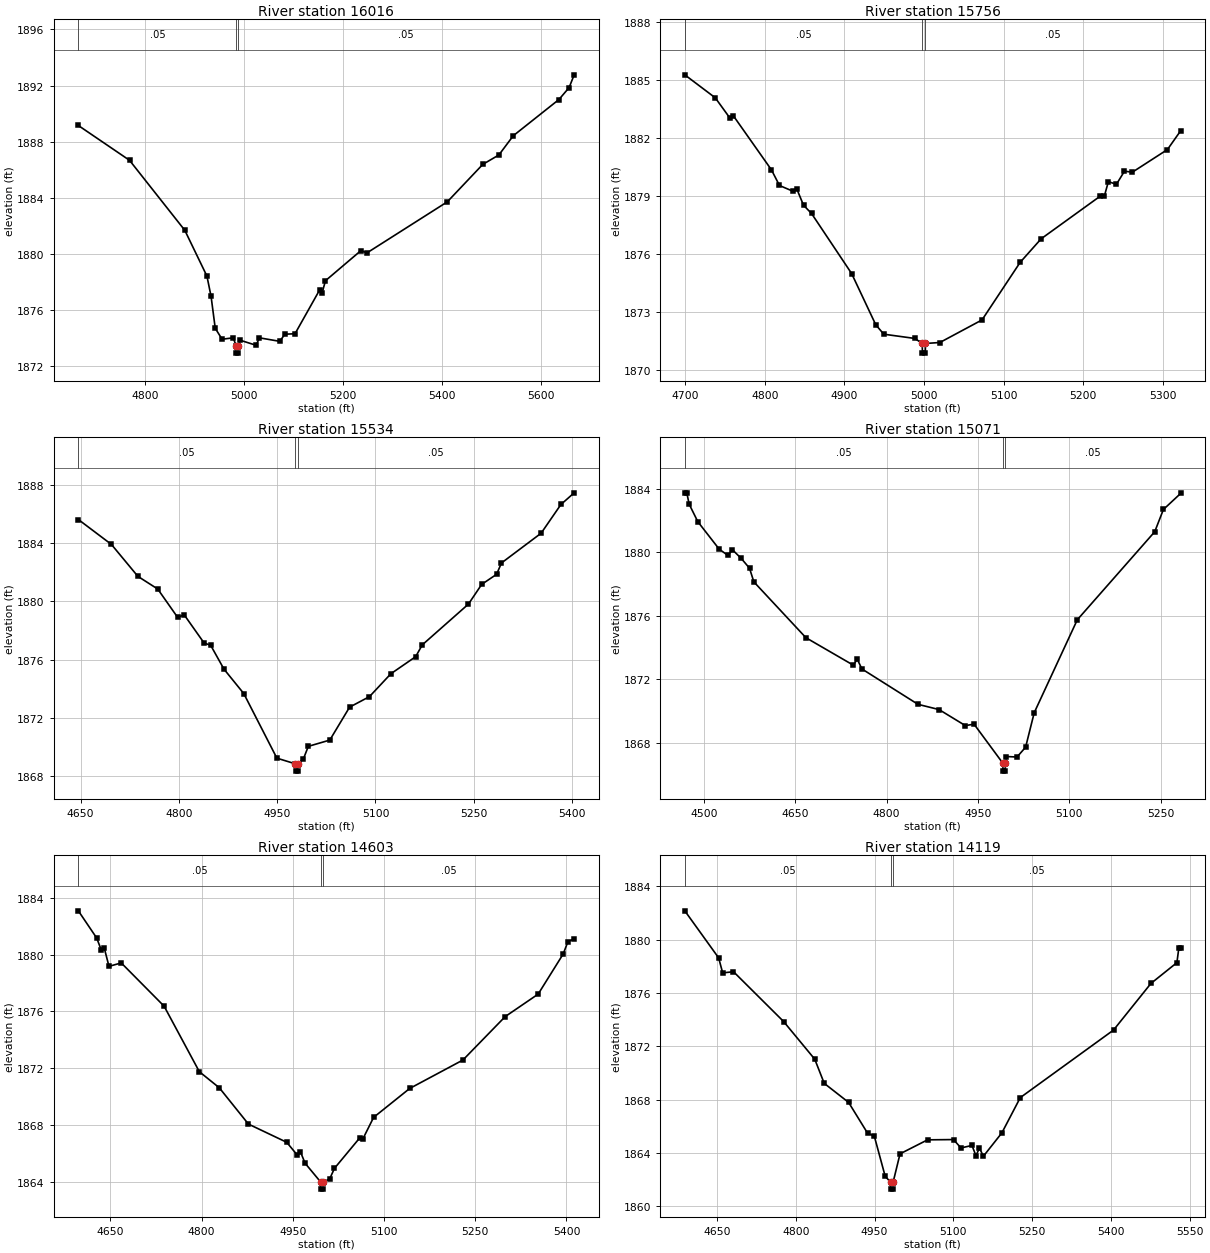
Type RM Length L Ch R = 1,16016,260,260,260
BEGIN DESCRIPTION:
Deadman 59 31.0
END DESCRIPTION:
XS GIS Cut Line= 3
      1633754.96      6848137.98      1634055.00      6848288.00
      1634704.96      6848437.99
#Sta/Elev= 30
  4664.8 1889.16  4768.3 1886.68  4880.1 1881.69  4924.8 1878.43  4933.2 1876.98
  4941.6 1874.71  4955.5 1873.93  4977.9 1874.03  4984.2 1873.44  4984.5 1872.94
  4988.0 1872.94  4988.3 1873.44  4991.9 1873.86  5024.2 1873.50  5031.0 1874.03
  5072.1 1873.78  5082.4 1874.29  5102.9 1874.32  5152.5 1877.43  5157.6 1877.22
  5164.5 1878.10  5236.3 1880.25  5248.3 1880.08  5410.8 1883.72  5482.6 1886.39
  5515.1 1887.06  5544.2 1888.43  5636.5 1891.01  5657.1 1891.86  5667.3 1892.77
#Mann=3,-1,0
  4664.8    0.05       0  4984.2    0.05       0  4988.3    0.05       0
Bank Sta=4984.2,4988.3
Exp/Cntr=0.3,0.1

Type RM Length L Ch R = 1,15756,222,222,222
BEGIN DESCRIPTION:
Mapping XS 0dc52cba
END DESCRIPTION:
XS GIS Cut Line= 2
      1633806.99      6848570.55      1634425.06      6848490.69
#Sta/Elev= 30
  4699.4 1885.28  4737.7 1884.09  4755.6 1883.07  4760.6 1883.15  4808.3 1880.36
  4818.4 1879.55  4834.9 1879.26  4840.0 1879.39  4848.6 1878.53  4858.7 1878.10
  4909.1 1874.99  4939.4 1872.34  4949.5 1871.85  4988.6 1871.63  4997.8 1871.37
  4998.1 1870.87  5001.7 1870.87  5001.9 1871.37  5020.0 1871.42  5073.0 1872.59
  5120.9 1875.57  5147.3 1876.79  5221.6 1879.00  5226.6 1878.98  5231.8 1879.75
  5241.9 1879.61  5252.0 1880.29  5262.0 1880.24  5306.0 1881.41  5322.6 1882.38
#Mann=3,-1,0
  4699.4    0.05       0  4997.8    0.03       0  5001.9    0.05       0
Bank Sta=4997.8,5001.9
Exp/Cntr=0.3,0.1

Type RM Length L Ch R = 1,15534,463,463,463
BEGIN DESCRIPTION:
Deadman 59 30.0
END DESCRIPTION:
XS GIS Cut Line= 3
      1633805.00      6848688.00      1634155.00      6848738.00
      1634555.03      6848688.00
#Sta/Elev= 30
  4646.5 1885.61  4697.0 1883.90  4737.4 1881.71  4767.7 1880.84  4798.0 1878.90
  4808.1 1879.07  4838.4 1877.14  4848.5 1876.98  4868.7 1875.35  4899.0 1873.67
  4949.5 1869.24  4977.8 1868.85  4978.0 1868.35  4981.6 1868.35  4981.9 1868.85
  4990.0 1869.19  4997.5 1870.05  5030.3 1870.48  5060.5 1872.74  5090.8 1873.46
  5123.5 1875.03  5161.3 1876.20  5171.4 1877.01  5241.9 1879.81  5262.1 1881.16
  5284.8 1881.85  5292.3 1882.63  5352.8 1884.67  5383.0 1886.64  5403.2 1887.44
#Mann=3,-1,0
  4646.5    0.05       0  4977.8    0.03       0  4981.9    0.05       0
Bank Sta=4977.8,4981.9
Exp/Cntr=0.3,0.1

Type RM Length L Ch R = 1,15071,468,468,468
BEGIN DESCRIPTION:
Deadman 59 29.0
END DESCRIPTION:
XS GIS Cut Line= 3
      1633954.99      6849488.01      1634355.00      6849138.00
      1634555.02      6848937.98
#Sta/Elev= 30
  4468.6 1883.75  4471.9 1883.75  4475.7 1883.04  4490.0 1881.93  4525.1 1880.20
  4539.3 1879.81  4546.9 1880.16  4561.2 1879.62  4574.9 1879.00  4582.0 1878.14
  4667.5 1874.62  4745.3 1872.89  4751.9 1873.26  4759.5 1872.65  4851.6 1870.42
  4886.2 1870.09  4929.4 1869.08  4943.7 1869.17  4991.0 1866.71  4991.2 1866.21
  4994.8 1866.21  4995.1 1866.71  4996.8 1867.13  5014.3 1867.10  5028.4 1867.72
  5042.5 1869.89  5113.3 1875.75  5240.5 1881.30  5254.7 1882.70  5283.0 1883.71
#Mann=3,-1,0
  4468.6    0.05       0  4991.0    0.05       0  4995.1    0.05       0
Bank Sta=4991,4995.1
Exp/Cntr=0.3,0.1

Type RM Length L Ch R = 1,14603,484,484,484
BEGIN DESCRIPTION:
Deadman 59 28.0
END DESCRIPTION:
XS GIS Cut Line= 3
      1634004.99      6849638.00      1634405.00      6849588.00
      1634804.97      6849488.01
#Sta/Elev= 30
  4597.2 1883.07  4627.4 1881.16  4635.0 1880.31  4640.0 1880.43  4647.6 1879.17
  4667.8 1879.41  4738.3 1876.37  4796.2 1871.77  4829.0 1870.64  4876.9 1868.09
  4939.9 1866.81  4957.5 1865.90  4962.5 1866.14  4970.1 1865.34  4995.7 1864.02
  4996.0 1863.52  4999.7 1863.52  5000.0 1864.02  5010.6 1864.24  5018.4 1864.98
  5059.6 1867.10  5064.7 1867.01  5082.8 1868.56  5142.1 1870.59  5229.7 1872.59
  5299.2 1875.64  5353.4 1877.22  5394.6 1880.04  5402.3 1880.90  5412.6 1881.11
#Mann=3,-1,0
  4597.2    0.05       0  4995.7    0.03       0  5000.0    0.05       0
Bank Sta=4995.7,5000
Exp/Cntr=0.3,0.1

Type RM Length L Ch R = 1,14119,459,459,459
BEGIN DESCRIPTION:
Deadman 59 27.0
END DESCRIPTION:
XS GIS Cut Line= 3
      1634005.03      6849938.01      1634405.00      6850038.00
      1634805.01      6849687.99
#Sta/Elev= 30
  4588.7 1882.17  4653.1 1878.64  4660.8 1877.51  4681.4 1877.60  4776.8 1873.86
  4836.1 1871.03  4854.1 1869.22  4900.5 1867.79  4936.6 1865.48  4949.4 1865.26
  4970.1 1862.25  4980.8 1861.78  4981.1 1861.28  4984.8 1861.28  4985.1 1861.78
  4998.4 1863.93  5050.8 1864.98  5100.2 1865.00  5114.4 1864.37  5135.3 1864.56
  5142.9 1863.79  5149.5 1864.36  5157.1 1863.75  5192.2 1865.50  5227.3 1868.15
  5404.8 1873.22  5476.0 1876.72  5525.4 1878.28  5529.2 1879.41  5532.5 1879.41
#Mann=3,-1,0
  4588.7    0.05       0  4980.8    0.05       0  4985.1    0.05       0
Bank Sta=4980.8,4985.1
Exp/Cntr=0.3,0.1

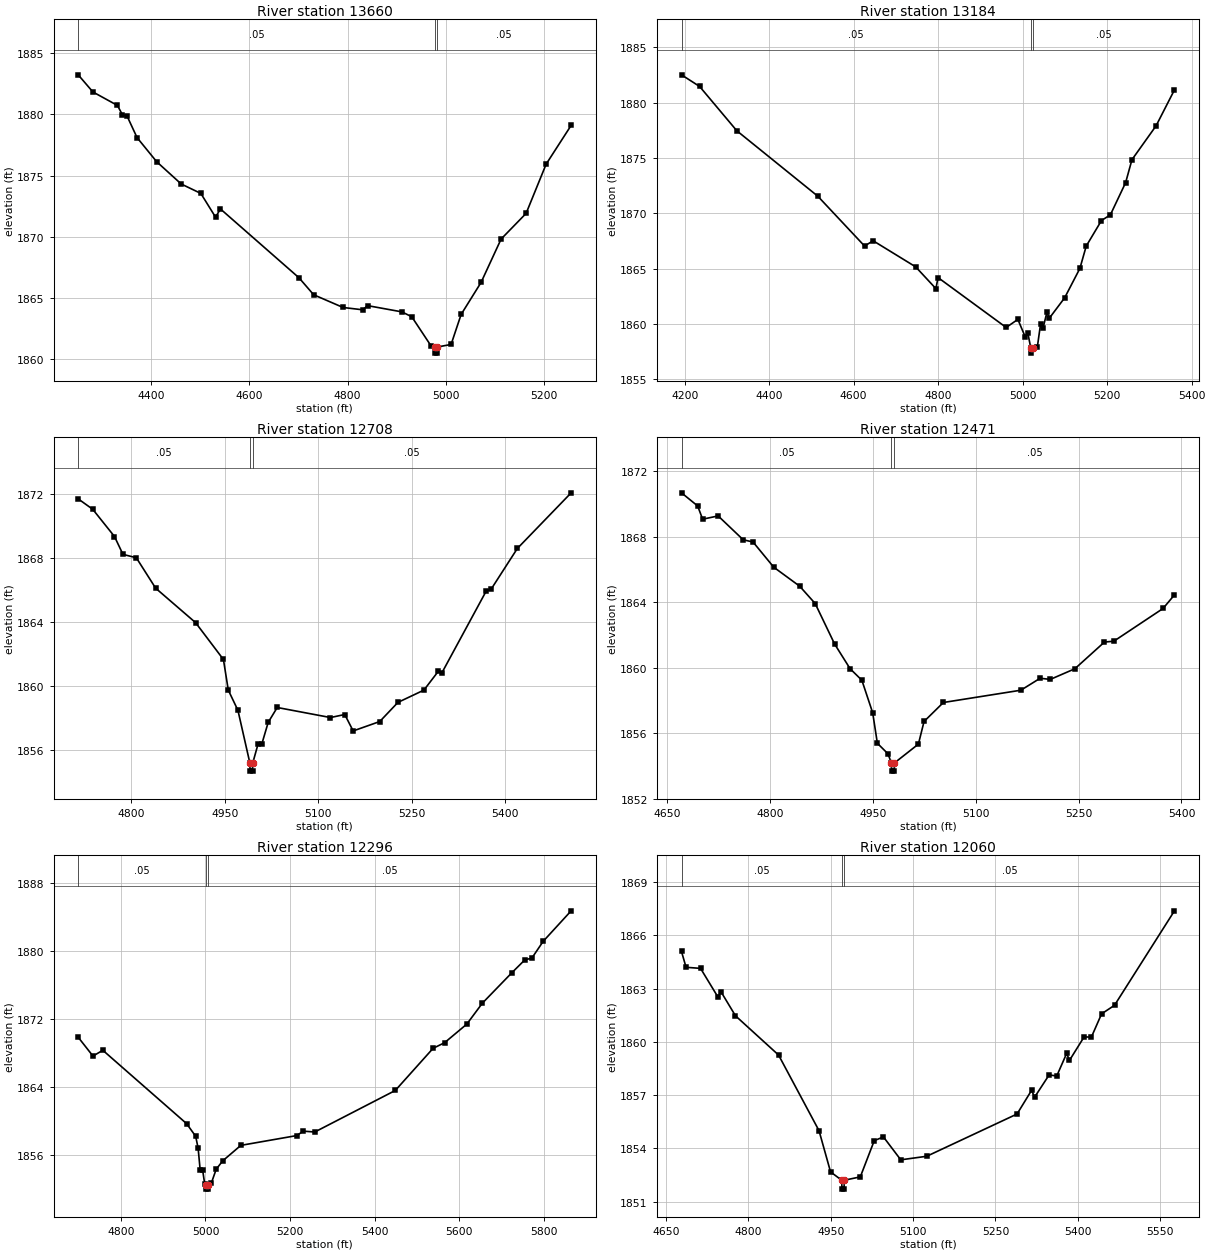
Type RM Length L Ch R = 1,13660,476,476,476
BEGIN DESCRIPTION:
Deadman 59 26.0
END DESCRIPTION:
XS GIS Cut Line= 3
      1633905.04      6850188.00      1634655.00      6850188.00
      1634904.99      6850238.00
#Sta/Elev= 30
  4250.9 1883.23  4280.9 1881.83  4330.9 1880.73  4340.9 1879.98  4350.9 1879.83
  4370.9 1878.10  4410.9 1876.13  4460.9 1874.31  4500.9 1873.54  4530.9 1871.60
  4540.9 1872.27  4700.9 1866.65  4730.9 1865.26  4790.9 1864.22  4830.9 1864.03
  4840.9 1864.37  4910.9 1863.86  4930.9 1863.46  4970.9 1861.04  4978.7 1860.99
  4979.0 1860.49  4982.8 1860.49  4983.1 1860.99  5011.1 1861.20  5031.5 1863.65
  5072.2 1866.27  5113.0 1869.81  5164.0 1871.91  5204.8 1875.93  5255.8 1879.10
#Mann=3,-1,0
  4250.9    0.05       0  4978.7    0.03       0  4983.1    0.05       0
Bank Sta=4978.7,4983.1
Exp/Cntr=0.3,0.1

Type RM Length L Ch R = 1,13184,476,476,476
BEGIN DESCRIPTION:
Deadman 59 25.0
END DESCRIPTION:
XS GIS Cut Line= 3
      1633855.04      6850738.00      1634655.00      6850638.00
      1634954.96      6850438.02
#Sta/Elev= 30
  4192.6 1882.52  4235.4 1881.47  4323.6 1877.46  4515.1 1871.55  4625.9 1867.04
  4646.1 1867.52  4746.8 1865.16  4794.7 1863.19  4799.8 1864.19  4961.0 1859.68
  4988.7 1860.41  5006.3 1858.81  5012.3 1859.16  5019.1 1857.86  5019.4 1857.36
  5023.5 1857.86  5034.8 1857.92  5042.4 1859.99  5048.4 1859.65  5057.4 1861.04
  5063.4 1860.53  5099.4 1862.36  5135.5 1865.02  5150.5 1867.04  5186.6 1869.35
  5207.6 1869.86  5243.7 1872.77  5258.7 1874.85  5315.8 1877.91  5359.3 1881.16
#Mann=3,-1,0
  4192.6    0.05       0  5019.1    0.03       0  5023.5    0.05       0
Bank Sta=5019.1,5023.5
Exp/Cntr=0.3,0.1

Type RM Length L Ch R = 1,12708,237,237,237
BEGIN DESCRIPTION:
Deadman 59 24.0
END DESCRIPTION:
XS GIS Cut Line= 3
      1634305.03      6851137.98      1634555.00      6850988.00
      1634954.99      6850688.01
#Sta/Elev= 30
  4714.5 1871.72  4737.8 1871.07  4772.8 1869.36  4786.4 1868.24  4807.8 1868.03
  4838.9 1866.12  4903.0 1863.96  4947.7 1861.65  4955.5 1859.73  4971.0 1858.46
  4990.2 1855.15  4990.5 1854.65  4994.4 1854.65  4994.7 1855.15  5003.1 1856.32
  5009.1 1856.32  5019.6 1857.71  5034.1 1858.64  5119.6 1858.01  5142.5 1858.20
  5156.0 1857.17  5198.7 1857.76  5227.9 1858.96  5269.6 1859.73  5292.5 1860.90
  5298.7 1860.83  5369.6 1865.94  5377.9 1866.08  5419.6 1868.61  5506.0 1872.10
#Mann=3,-1,0
  4714.5    0.05       0  4990.2    0.05       0  4994.7    0.05       0
Bank Sta=4990.2,4994.7
Exp/Cntr=0.3,0.1

Type RM Length L Ch R = 1,12471,175,175,175
BEGIN DESCRIPTION:
Mapping XS f86ecc61
END DESCRIPTION:
XS GIS Cut Line= 3
      1634393.83      6851317.06      1634827.82      6851108.75
      1634963.21      6850914.34
#Sta/Elev= 30
  4671.5 1870.67  4695.0 1869.87  4702.3 1869.06  4724.9 1869.26  4761.5 1867.80
  4775.7 1867.67  4805.9 1866.13  4843.7 1864.97  4866.3 1863.91  4894.6 1861.44
  4917.2 1859.93  4934.3 1859.23  4950.1 1857.24  4956.9 1855.38  4972.3 1854.74
  4977.3 1854.18  4977.6 1853.68  4981.5 1853.68  4981.8 1854.18  5016.7 1855.33
  5024.9 1856.71  5053.1 1857.87  5166.0 1858.62  5194.1 1859.35  5208.9 1859.28
  5244.7 1859.93  5287.8 1861.56  5301.4 1861.61  5373.2 1863.61  5389.8 1864.44
#Mann=3,-1,0
  4671.5    0.05       0  4977.3    0.03       0  4981.8    0.05       0
Bank Sta=4977.3,4981.8
Exp/Cntr=0.3,0.1

Type RM Length L Ch R = 1,12296,236,236,236
BEGIN DESCRIPTION:
Deadman 59 23.0
END DESCRIPTION:
XS GIS Cut Line= 3
      1634505.02      6851487.99      1634755.00      6851338.00
      1635205.02      6850587.97
#Sta/Elev= 30
  4698.9 1869.86  4733.9 1867.65  4757.2 1868.33  4955.4 1859.71  4976.8 1858.23
  4982.6 1856.84  4987.5 1854.26  4993.3 1854.26  4998.2 1852.62  5001.8 1852.52
  5002.1 1852.02  5006.0 1852.02  5006.3 1852.52  5013.7 1852.70  5025.4 1854.36
  5041.0 1855.35  5083.7 1857.16  5215.9 1858.31  5231.4 1858.83  5258.6 1858.73
  5449.1 1863.61  5538.5 1868.56  5565.7 1869.22  5618.2 1871.40  5655.2 1873.87
  5725.1 1877.45  5756.2 1878.98  5771.8 1879.13  5799.0 1881.13  5865.1 1884.71
#Mann=3,-1,0
  4698.9    0.05       0  5001.8    0.05       0  5006.3    0.05       0
Bank Sta=5001.8,5006.3
Exp/Cntr=0.3,0.1

Type RM Length L Ch R = 1,12060,219,219,219
BEGIN DESCRIPTION:
Mapping XS 028a6011
END DESCRIPTION:
XS GIS Cut Line= 3
      1634657.08      6851593.88      1634930.67      6851503.84
      1635120.42      6850924.23
#Sta/Elev= 30
  4678.2 1865.09  4686.5 1864.20  4712.9 1864.14  4744.7 1862.52  4750.0 1862.83
  4776.5 1861.47  4855.0 1859.26  4928.7 1855.00  4949.7 1852.68  4970.1 1852.21
  4970.4 1851.71  4974.3 1851.71  4974.6 1852.21  5003.9 1852.40  5029.3 1854.44
  5046.0 1854.65  5077.6 1853.36  5124.9 1853.56  5289.4 1855.94  5316.0 1857.28
  5321.2 1856.88  5347.8 1858.14  5361.7 1858.08  5379.7 1859.35  5384.9 1858.96
  5411.5 1860.28  5424.8 1860.27  5443.4 1861.58  5466.9 1862.06  5576.1 1867.38
#Mann=3,-1,0
  4678.2    0.05       0  4970.1    0.05       0  4974.6    0.05       0
Bank Sta=4970.1,4974.6
Exp/Cntr=0.3,0.1

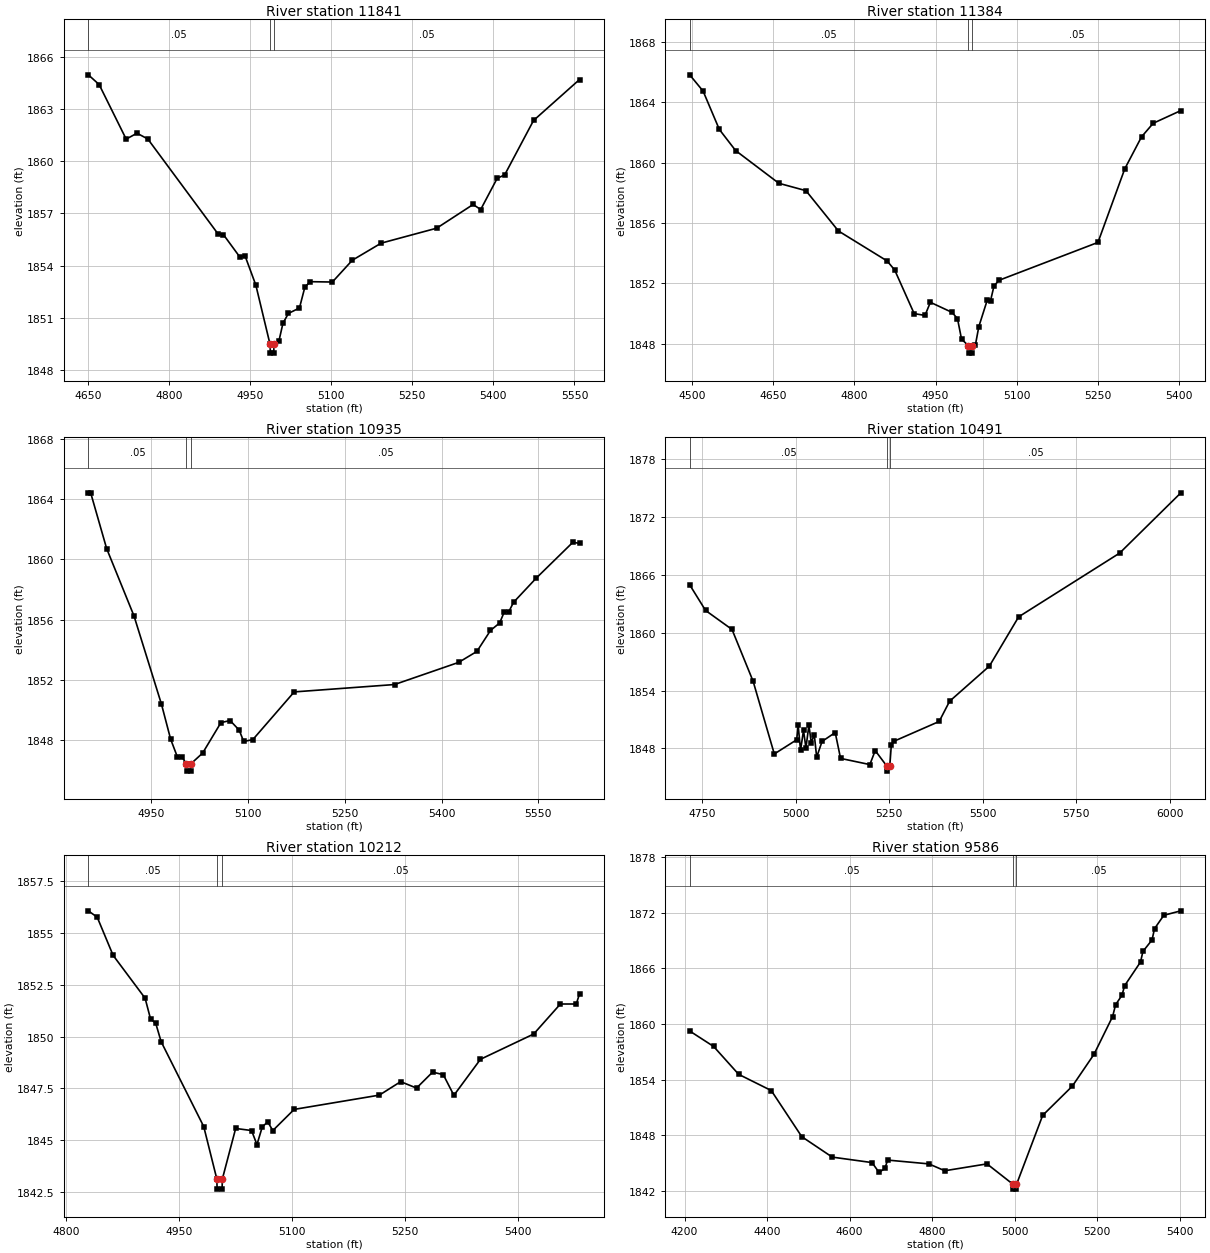
Type RM Length L Ch R = 1,11841,457,457,457
BEGIN DESCRIPTION:
Deadman 59 22.0
END DESCRIPTION:
XS GIS Cut Line= 3
      1634655.01      6851638.00      1635005.00      6851638.00
      1635554.99      6851738.00
#Sta/Elev= 30
  4650.4 1864.95  4670.4 1864.39  4720.4 1861.26  4740.4 1861.60  4760.4 1861.27
  4890.4 1855.82  4900.4 1855.78  4930.4 1854.51  4940.4 1854.56  4960.4 1852.88
  4986.7 1849.48  4987.2 1848.98  4993.5 1848.98  4994.0 1849.48  5002.9 1849.65
  5010.6 1850.70  5020.7 1851.26  5041.1 1851.57  5051.2 1852.78  5061.4 1853.08
  5102.0 1853.06  5138.9 1854.31  5192.2 1855.29  5295.1 1856.15  5362.5 1857.51
  5376.5 1857.22  5407.0 1859.01  5420.9 1859.21  5474.3 1862.33  5559.4 1864.68
#Mann=3,-1,0
  4650.4    0.05       0  4986.7    0.05       0  4994.0    0.05       0
Bank Sta=4986.7,4994
Exp/Cntr=0.3,0.1

Type RM Length L Ch R = 1,11384,449,449,449
BEGIN DESCRIPTION:
Deadman 59 21.0
END DESCRIPTION:
XS GIS Cut Line= 3
      1634650.21      6852057.87      1635155.00      6852038.00
      1635505.01      6851838.00
#Sta/Elev= 30
  4495.3 1865.82  4520.1 1864.74  4550.1 1862.20  4580.2 1860.80  4660.2 1858.63
  4710.3 1858.14  4770.3 1855.47  4860.4 1853.48  4874.4 1852.88  4910.4 1849.99
  4930.4 1849.87  4940.4 1850.74  4980.5 1850.07  4990.5 1849.66  4998.0 1848.30
  5010.5 1847.87  5011.0 1847.37  5017.3 1847.37  5017.8 1847.87  5023.5 1847.88
  5030.0 1849.13  5045.8 1850.91  5051.6 1850.84  5058.1 1851.83  5067.4 1852.20
  5250.3 1854.71  5299.9 1859.59  5330.9 1861.71  5352.5 1862.61  5403.6 1863.45
#Mann=3,-1,0
  4495.3    0.05       0  5010.5    0.05       0  5017.8    0.05       0
Bank Sta=5010.5,5017.8
Exp/Cntr=0.3,0.1

Type RM Length L Ch R = 1,10935,444,444,444
BEGIN DESCRIPTION:
Deadman 59 20.0
END DESCRIPTION:
XS GIS Cut Line= 3
      1635104.99      6852538.01      1635205.00      6852438.00
      1635626.67      6851985.16
#Sta/Elev= 30
  4853.4 1864.42  4857.0 1864.42  4881.7 1860.72  4924.1 1856.24  4966.6 1850.38
  4980.7 1848.07  4991.3 1846.87  4998.3 1846.87  5005.1 1846.44  5005.6 1845.94
  5012.0 1845.94  5012.5 1846.44  5030.3 1847.14  5058.6 1849.16  5072.8 1849.30
  5086.9 1848.66  5093.8 1847.91  5107.9 1848.03  5172.0 1851.20  5327.3 1851.69
  5426.5 1853.16  5454.8 1853.89  5475.8 1855.28  5490.0 1855.78  5497.3 1856.53
  5504.2 1856.53  5511.5 1857.15  5546.7 1858.76  5603.4 1861.14  5613.6 1861.06
#Mann=3,-1,0
  4853.4    0.05       0  5005.1    0.05       0  5012.5    0.05       0
Bank Sta=5005.1,5012.5
Exp/Cntr=0.3,0.1

Type RM Length L Ch R = 1,10491,279,279,279
BEGIN DESCRIPTION:
Deadman 59 19.0
END DESCRIPTION:
XS GIS Cut Line= 3
      1635354.98      6852838.02      1635555.00      6852638.00
      1636204.97      6851838.03
#Sta/Elev= 30
  4716.3 1864.97  4758.8 1862.31  4829.5 1860.34  4886.0 1854.96  4942.6 1847.43
  5002.4 1848.90  5006.4 1850.39  5012.8 1847.81  5020.7 1849.88  5027.2 1848.05
  5035.1 1850.41  5041.5 1848.61  5049.5 1849.43  5055.9 1847.10  5070.3 1848.73
  5105.5 1849.65  5119.8 1846.97  5198.1 1846.33  5212.5 1847.78  5243.9 1846.15
  5244.4 1845.65  5251.4 1846.15  5255.6 1848.39  5262.1 1848.74  5383.5 1850.80
  5411.5 1852.90  5517.8 1856.54  5596.1 1861.65  5866.2 1868.26  6029.9 1874.51
#Mann=3,-1,0
  4716.3    0.05       0  5243.9    0.05       0  5251.4    0.05       0
Bank Sta=5243.9,5251.4
Exp/Cntr=0.3,0.1

Type RM Length L Ch R = 1,10212,626,626,626
BEGIN DESCRIPTION:
Mapping XS 019cfd76
END DESCRIPTION:
XS GIS Cut Line= 2
      1635661.15      6852910.84      1636115.55      6852442.56
#Sta/Elev= 30
  4829.6 1856.07  4841.4 1855.76  4862.5 1853.92  4905.0 1851.85  4912.2 1850.85
  4919.1 1850.64  4926.3 1849.75  4982.9 1845.65  5000.2 1843.13  5000.7 1842.63
  5007.2 1842.63  5007.7 1843.13  5025.3 1845.56  5046.4 1845.46  5053.6 1844.78
  5060.6 1845.63  5067.8 1845.88  5074.7 1845.46  5103.0 1846.48  5216.2 1847.17
  5244.5 1847.82  5265.6 1847.51  5286.9 1848.28  5301.1 1848.16  5315.2 1847.16
  5350.5 1848.90  5421.2 1850.12  5456.7 1851.57  5477.8 1851.57  5482.1 1852.06
#Mann=3,-1,0
  4829.6    0.05       0  5000.2    0.03       0  5007.7    0.05       0
Bank Sta=5000.2,5007.7
Exp/Cntr=0.3,0.1

Type RM Length L Ch R = 1,9586,491,491,491
BEGIN DESCRIPTION:
Mapping XS 2641436b
END DESCRIPTION:
XS GIS Cut Line= 3
      1635598.95      6852930.47      1636062.97      6853058.60
      1636691.60      6852730.47
#Sta/Elev= 30
  4212.3 1859.25  4270.4 1857.58  4331.0 1854.58  4410.1 1852.83  4484.0 1847.86
  4557.8 1845.66  4654.3 1845.07  4671.3 1844.01  4685.4 1844.44  4692.1 1845.34
  4792.0 1844.93  4830.6 1844.19  4932.9 1844.93  4996.6 1842.71  4997.1 1842.21
  5003.9 1842.21  5004.4 1842.71  5067.9 1850.16  5139.8 1853.31  5192.3 1856.74
  5237.4 1860.81  5244.6 1862.08  5260.0 1863.10  5266.6 1864.14  5305.1 1866.69
  5310.8 1867.82  5332.9 1869.06  5339.0 1870.28  5361.5 1871.72  5402.8 1872.20
#Mann=3,-1,0
  4212.3    0.05       0  4996.6    0.03       0  5004.4    0.05       0
Bank Sta=4996.6,5004.4
Exp/Cntr=0.3,0.1

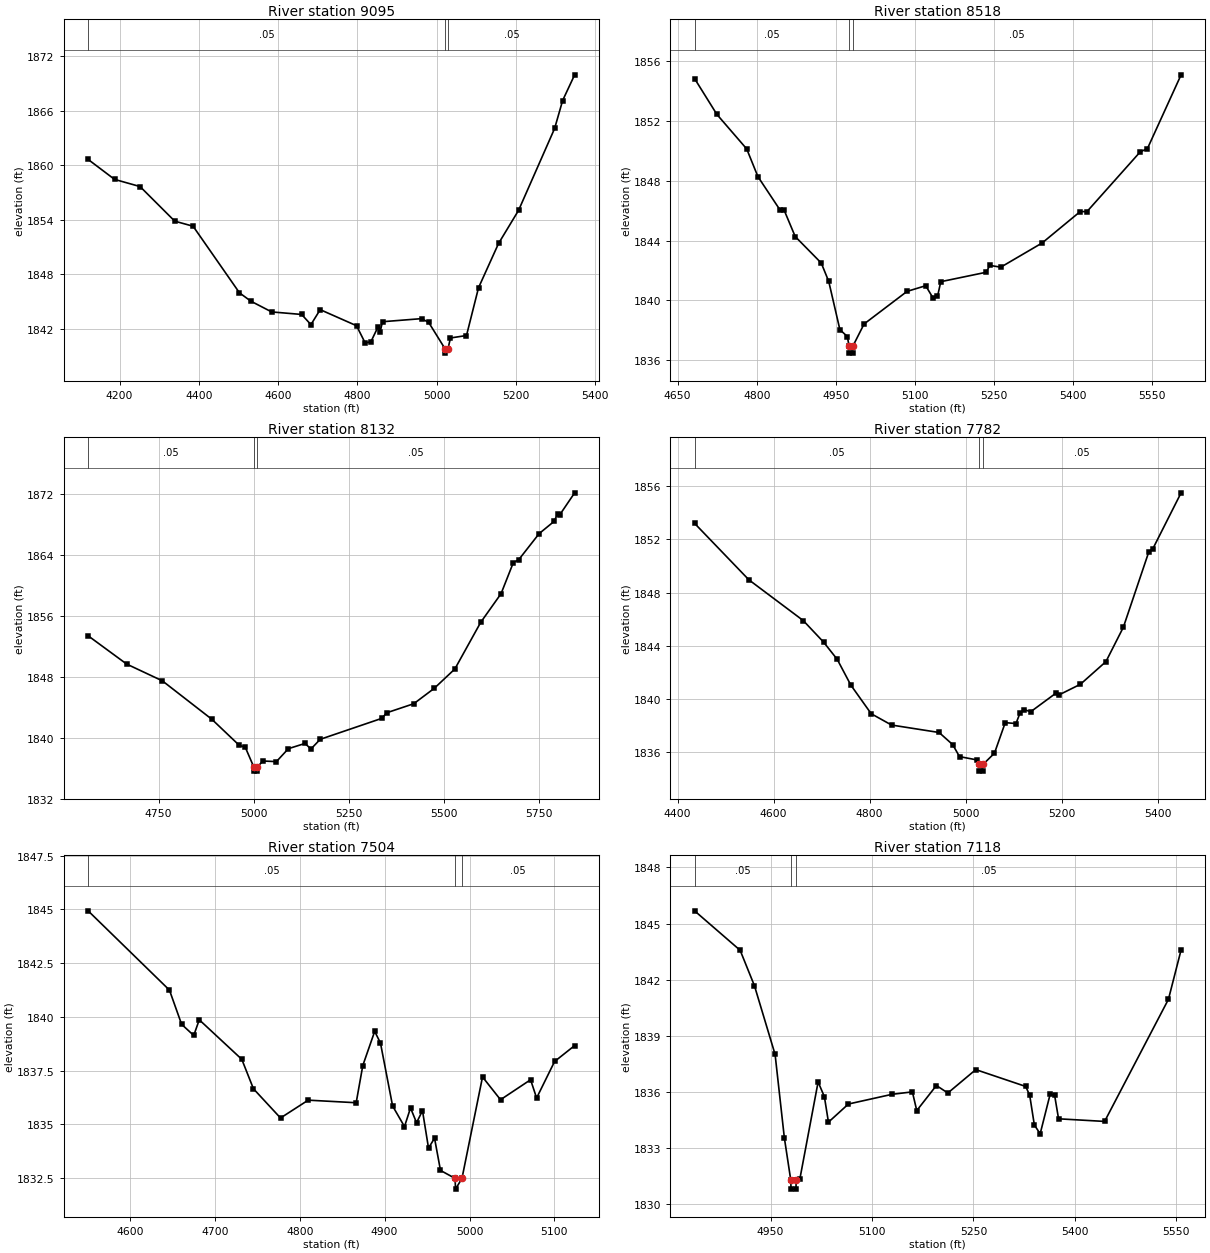
Type RM Length L Ch R = 1,9095,577,577,577
BEGIN DESCRIPTION:
Deadman 59 18.0
END DESCRIPTION:
XS GIS Cut Line= 3
      1635554.95      6852987.98      1636355.00      6853338.00
      1636704.98      6853288.00
#Sta/Elev= 30
  4120.8 1860.64  4187.5 1858.44  4251.8 1857.65  4339.2 1853.84  4385.5 1853.28
  4502.5 1845.94  4531.3 1845.02  4583.6 1843.84  4659.2 1843.56  4682.6 1842.44
  4706.0 1844.09  4797.6 1842.32  4819.4 1840.42  4833.8 1840.55  4851.8 1842.19
  4857.2 1841.67  4863.1 1842.76  4961.7 1843.10  4979.6 1842.68  5020.5 1839.80
  5021.0 1839.30  5028.3 1839.80  5034.5 1840.97  5074.9 1841.24  5105.2 1846.50
  5155.7 1851.38  5206.2 1855.03  5297.1 1864.05  5317.3 1867.13  5347.6 1869.96
#Mann=3,-1,0
  4120.8    0.05       0  5020.5    0.05       0  5028.3    0.05       0
Bank Sta=5020.5,5028.3
Exp/Cntr=0.3,0.1

Type RM Length L Ch R = 1,8518,386,386,386
BEGIN DESCRIPTION:
Deadman 59 17.0
END DESCRIPTION:
XS GIS Cut Line= 3
      1635704.97      6853287.97      1635934.85      6853515.68
      1636405.01      6853888.01
#Sta/Elev= 30
  4682.1 1854.84  4724.5 1852.44  4781.1 1850.13  4802.3 1848.28  4844.8 1846.02
  4851.8 1846.06  4873.1 1844.27  4922.5 1842.50  4936.7 1841.27  4957.9 1838.04
  4972.1 1837.58  4975.1 1836.97  4975.6 1836.47  4982.5 1836.47  4983.0 1836.97
  5003.8 1838.42  5085.3 1840.60  5120.7 1840.98  5135.0 1840.14  5143.1 1840.26
  5149.4 1841.25  5235.5 1841.88  5242.4 1842.34  5263.2 1842.22  5341.7 1843.84
  5413.9 1845.94  5426.8 1845.94  5527.7 1849.93  5541.6 1850.16  5605.4 1855.09
#Mann=3,-1,0
  4682.1    0.05       0  4975.1    0.03       0  4983.0    0.05       0
Bank Sta=4975.1,4983
Exp/Cntr=0.3,0.1

Type RM Length L Ch R = 1,8132,350,350,350
BEGIN DESCRIPTION:
Deadman 59 16.0
END DESCRIPTION:
XS GIS Cut Line= 3
      1635354.96      6853587.98      1635744.40      6853837.71
      1636505.04      6854138.01
#Sta/Elev= 30
  4564.5 1853.39  4666.0 1849.67  4759.8 1847.47  4890.0 1842.42  4962.7 1838.97
  4977.9 1838.76  5000.9 1836.10  5001.4 1835.60  5008.5 1835.60  5009.0 1836.10
  5024.5 1836.93  5060.0 1836.85  5091.5 1838.55  5135.3 1839.24  5150.9 1838.51
  5175.3 1839.78  5337.6 1842.54  5350.3 1843.27  5421.5 1844.46  5475.6 1846.49
  5529.7 1849.03  5597.6 1855.15  5651.3 1858.93  5683.6 1863.02  5697.4 1863.37
  5751.5 1866.82  5791.1 1868.44  5800.2 1869.45  5805.6 1869.28  5844.9 1872.18
#Mann=3,-1,0
  4564.5    0.05       0  5000.9    0.05       0  5009.0    0.05       0
Bank Sta=5000.9,5009
Exp/Cntr=0.3,0.1

Type RM Length L Ch R = 1,7782,278,278,278
BEGIN DESCRIPTION:
Deadman 59 15.0
END DESCRIPTION:
XS GIS Cut Line= 3
      1635254.99      6853737.99      1635655.00      6854138.00
      1636054.99      6854337.99
#Sta/Elev= 30
  4435.5 1853.20  4548.6 1848.96  4661.8 1845.90  4704.2 1844.28  4732.5 1842.99
  4760.8 1841.06  4803.2 1838.91  4845.6 1838.06  4944.6 1837.50  4972.9 1836.59
  4987.1 1835.69  5023.6 1835.44  5027.9 1835.10  5028.4 1834.60  5035.5 1834.60
  5036.0 1835.10  5059.9 1835.95  5082.3 1838.24  5104.6 1838.17  5113.0 1838.95
  5121.4 1839.22  5135.4 1839.06  5188.5 1840.47  5194.1 1840.32  5238.8 1841.12
  5291.9 1842.82  5328.2 1845.40  5381.3 1851.07  5389.7 1851.30  5448.4 1855.49
#Mann=3,-1,0
  4435.5    0.05       0  5027.9    0.03       0  5036.0    0.05       0
Bank Sta=5027.9,5036
Exp/Cntr=0.3,0.1

Type RM Length L Ch R = 1,7504,386,386,386
BEGIN DESCRIPTION:
Mapping XS 60c22960
END DESCRIPTION:
XS GIS Cut Line= 3
      1635268.77      6854039.27      1635501.43      6854317.08
      1635650.37      6854466.02
#Sta/Elev= 30
  4550.8 1844.93  4646.6 1841.24  4660.9 1839.65  4675.2 1839.13  4681.7 1839.86
  4731.8 1838.02  4745.5 1836.65  4777.4 1835.29  4810.0 1836.12  4866.5 1836.00
  4874.3 1837.73  4888.3 1839.32  4895.1 1838.78  4909.4 1835.85  4923.4 1834.89
  4930.5 1835.76  4937.6 1835.07  4944.6 1835.63  4951.7 1833.89  4958.8 1834.35
  4965.8 1832.85  4983.0 1832.48  4983.5 1831.98  4991.1 1832.48  5015.3 1837.20
  5036.5 1836.14  5071.9 1837.07  5079.0 1836.22  5100.2 1837.92  5123.8 1838.66
#Mann=3,-1,0
  4550.8    0.05       0  4983.0    0.03       0  4991.1    0.05       0
Bank Sta=4983,4991.1
Exp/Cntr=0.3,0.1

Type RM Length L Ch R = 1,7118,213,213,213
BEGIN DESCRIPTION:
Mapping XS bf6ff628
END DESCRIPTION:
XS GIS Cut Line= 3
      1635154.21      6854115.69      1635352.53      6854429.70
      1635651.04      6854608.78
#Sta/Elev= 30
  4837.6 1845.68  4905.0 1843.57  4926.2 1841.67  4956.7 1838.00  4970.4 1833.54
  4979.8 1831.30  4980.3 1830.80  4987.5 1830.80  4988.0 1831.30  4993.2 1831.32
  5020.3 1836.53  5029.6 1835.74  5035.6 1834.38  5065.1 1835.35  5129.7 1835.87
  5159.7 1836.00  5166.2 1835.00  5195.2 1836.34  5212.2 1835.94  5253.5 1837.19
  5327.3 1836.29  5333.2 1835.82  5340.1 1834.23  5348.7 1833.76  5363.5 1835.88
  5370.1 1835.81  5375.9 1834.56  5444.0 1834.42  5538.4 1840.95  5557.1 1843.59
#Mann=3,-1,0
  4837.6    0.05       0  4979.8    0.05       0  4988.0    0.05       0
Bank Sta=4979.8,4988
Exp/Cntr=0.3,0.1