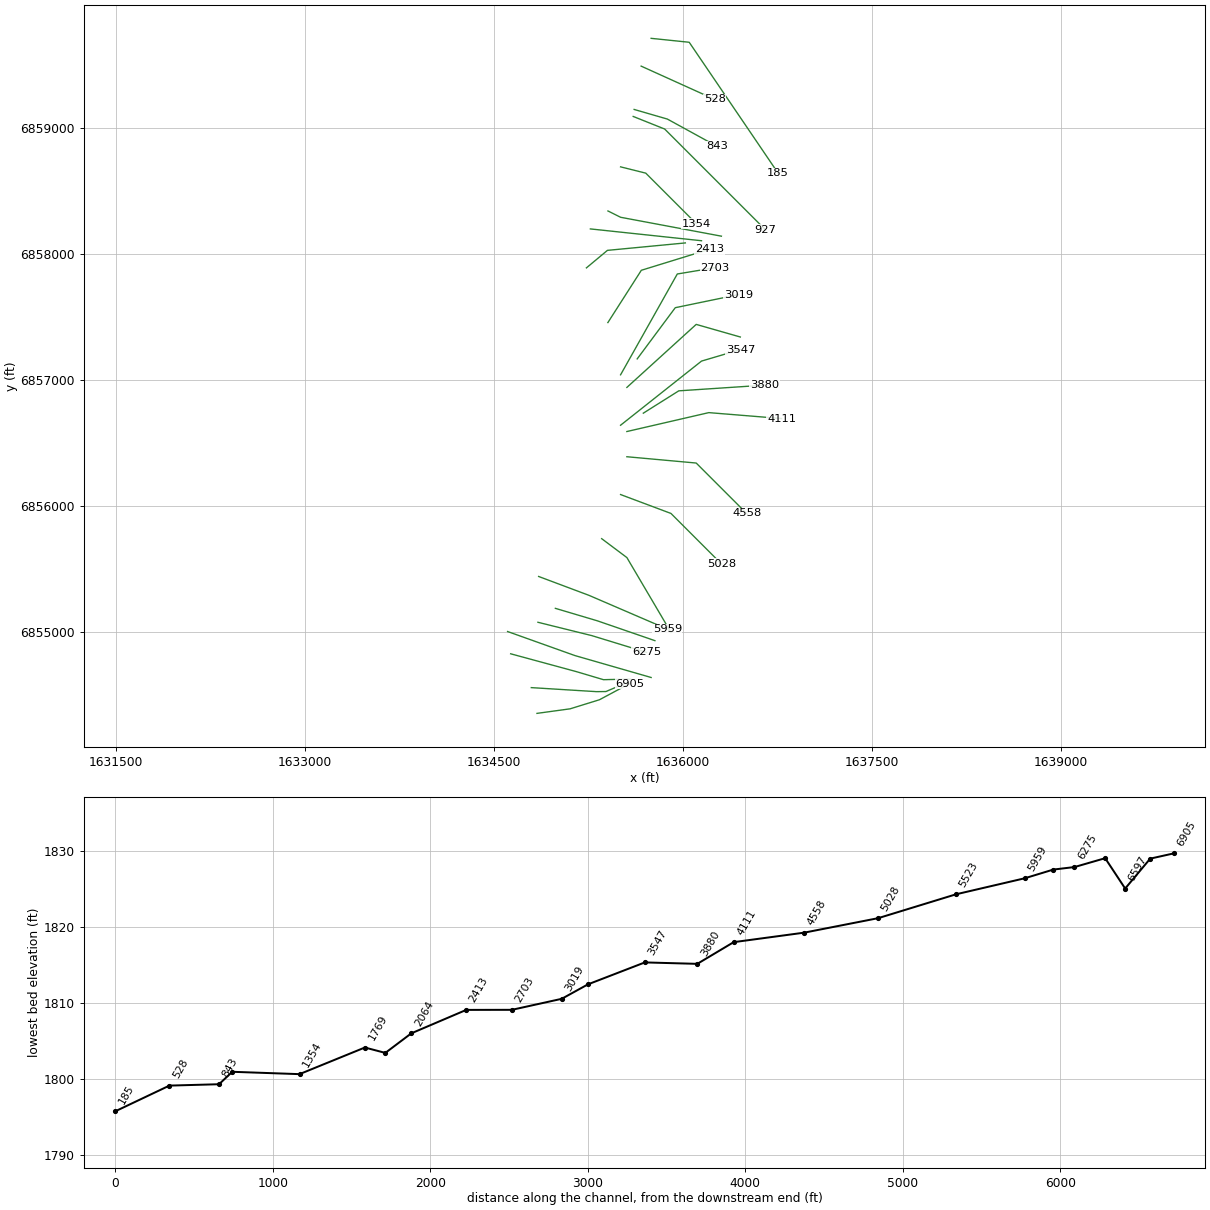
HEC-RAS study Deadman 59.prj: Deadman 59 Base Level Engineering

--- Deadman 59.g01 (geometry) --- (continued)

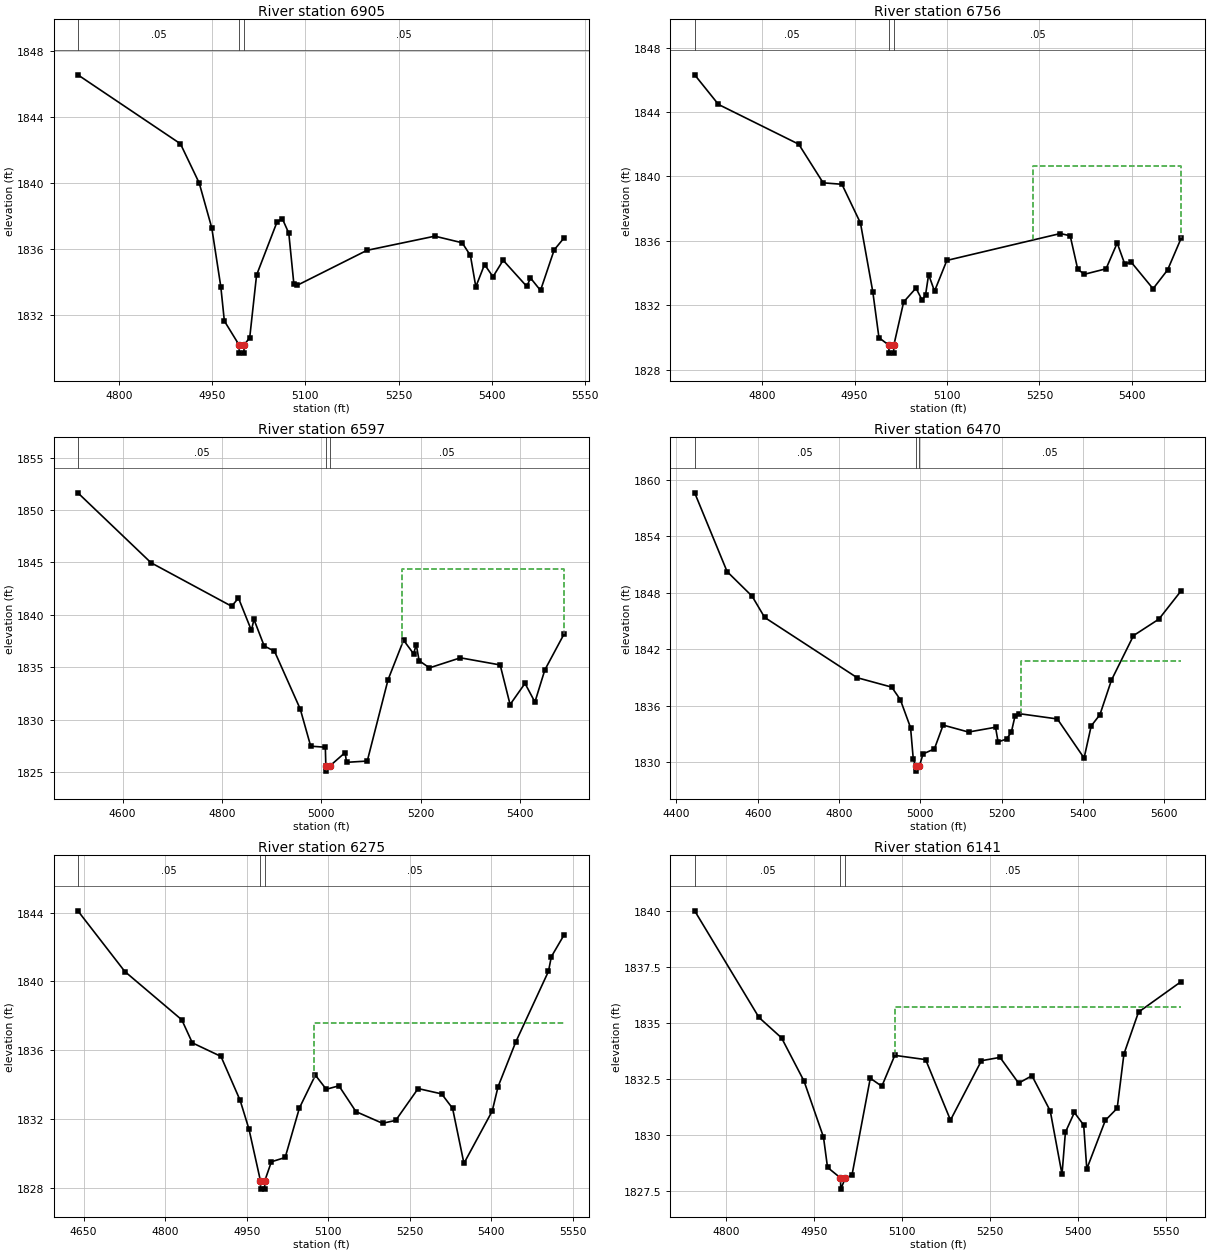
Type RM Length L Ch R = 1,6905,149,149,149
BEGIN DESCRIPTION:
Deadman 59 14.0
END DESCRIPTION:
XS GIS Cut Line= 4
      1634841.69      6854351.80      1635105.00      6854388.00
      1635337.32      6854459.90      1635578.08      6854588.64
#Sta/Elev= 30
  4734.2 1846.58  4899.1 1842.40  4929.3 1840.02  4949.5 1837.30  4964.0 1833.74
  4969.7 1831.66  4993.3 1830.21  4993.8 1829.71  5001.1 1829.71  5001.6 1830.21
  5010.5 1830.65  5021.5 1834.44  5054.1 1837.63  5062.8 1837.87  5073.3 1836.98
  5081.5 1833.89  5086.8 1833.82  5198.9 1835.94  5308.1 1836.80  5352.0 1836.40
  5365.3 1835.63  5374.0 1833.73  5388.0 1835.08  5401.6 1834.34  5417.9 1835.34
  5456.0 1833.75  5461.8 1834.27  5478.0 1833.51  5500.0 1835.97  5516.2 1836.71
#Mann=3,-1,0
  4734.2    0.05       0  4993.3    0.05       0  5001.6    0.05       0
Bank Sta=4993.3,5001.6
Exp/Cntr=0.3,0.1

Type RM Length L Ch R = 1,6756,159,159,159
BEGIN DESCRIPTION:
Mapping XS 8c6d95fc
END DESCRIPTION:
XS GIS Cut Line= 4
      1634796.46      6854556.15      1635313.65      6854524.18
      1635388.98      6854525.12      1635569.27      6854601.97
#Sta/Elev= 30
  4690.4 1846.31  4729.0 1844.47  4859.3 1842.00  4898.9 1839.60  4929.4 1839.51
  4959.5 1837.10  4979.5 1832.83  4989.5 1829.98  5005.4 1829.52  5005.9 1829.02
  5013.2 1829.02  5013.7 1829.52  5029.6 1832.20  5049.6 1833.06  5059.6 1832.31
  5065.1 1832.63  5070.1 1833.90  5079.7 1832.87  5099.7 1834.78  5283.9 1836.45
  5299.9 1836.31  5312.2 1834.22  5323.1 1833.92  5358.1 1834.26  5376.2 1835.86
  5388.3 1834.57  5399.2 1834.66  5434.4 1833.02  5458.0 1834.19  5479.9 1836.15
#Mann=3,-1,0
  4690.4    0.05       0  5005.4    0.05       0  5013.7    0.05       0
#XS Ineff=2,0
       0                 5240.30    0.00 1840.64
Permanent Ineff=
       F       F
Bank Sta=5005.4,5013.7
Exp/Cntr=0.3,0.1

Type RM Length L Ch R = 1,6597,127,127,127
BEGIN DESCRIPTION:
Mapping XS b45a237d
END DESCRIPTION:
XS GIS Cut Line= 4
      1634632.89      6854824.58      1635155.74      6854682.61
      1635369.58      6854619.04      1635584.05      6854624.13
#Sta/Elev= 30
  4509.8 1851.63  4657.1 1844.96  4819.4 1840.81  4833.2 1841.59  4859.2 1838.51
  4864.4 1839.55  4885.0 1837.02  4905.7 1836.52  4957.6 1831.00  4978.6 1827.46
  5008.1 1827.36  5009.1 1825.58  5009.6 1825.08  5017.4 1825.58  5047.9 1826.85
  5050.8 1825.92  5092.5 1826.04  5134.3 1833.79  5165.6 1837.57  5185.9 1836.27
  5191.1 1837.16  5196.9 1835.62  5217.7 1834.93  5280.1 1835.89  5360.1 1835.21
  5380.1 1831.43  5410.1 1833.45  5430.1 1831.67  5450.1 1834.74  5489.2 1838.20
#Mann=3,-1,0
  4509.8    0.05       0  5009.1    0.05       0  5017.4    0.05       0
#XS Ineff=2,0
       0                 5161.60    0.00 1844.37
Permanent Ineff=
       F       F
Bank Sta=5009.1,5017.4
Exp/Cntr=0.3,0.1

Type RM Length L Ch R = 1,6470,195,195,195
BEGIN DESCRIPTION:
Deadman 59 13.0
END DESCRIPTION:
XS GIS Cut Line= 4
      1634608.67      6855001.17      1635141.89      6854810.73
      1635421.57      6854730.27      1635747.52      6854636.51
#Sta/Elev= 30
  4444.8 1858.63  4524.5 1850.27  4586.1 1847.65  4616.9 1845.40  4844.4 1839.00
  4929.4 1838.00  4950.6 1836.67  4975.8 1833.69  4982.5 1830.34  4988.9 1829.58
  4989.4 1829.08  4997.2 1829.58  5006.6 1830.91  5034.4 1831.44  5055.9 1833.97
  5118.3 1833.23  5184.8 1833.74  5191.1 1832.18  5211.9 1832.49  5223.7 1833.22
  5232.8 1834.95  5243.2 1835.18  5336.8 1834.62  5402.6 1830.47  5420.1 1833.88
  5441.5 1835.07  5470.0 1838.75  5524.1 1843.47  5586.6 1845.22  5641.2 1848.22
#Mann=3,-1,0
  4444.8    0.05       0  4988.9    0.05       0  4997.2    0.05       0
#XS Ineff=2,0
    0.00 4753.10 1840.76 5246.90    0.00 1840.76
Permanent Ineff=
       F       F
Bank Sta=4988.9,4997.2
Exp/Cntr=0.3,0.1

Type RM Length L Ch R = 1,6275,134,134,134
BEGIN DESCRIPTION:
Mapping XS e0da5233
END DESCRIPTION:
XS GIS Cut Line= 3
      1634849.41      6855074.59      1635277.23      6854968.61
      1635711.46      6854835.61
#Sta/Elev= 30
  4639.5 1844.10  4725.9 1840.57  4830.7 1837.76  4850.1 1836.42  4902.8 1835.63
  4938.1 1833.07  4954.3 1831.40  4975.3 1828.41  4975.8 1827.91  4983.1 1827.91
  4983.6 1828.41  4995.5 1829.50  5020.9 1829.75  5047.1 1832.63  5076.5 1834.54
  5096.5 1833.72  5119.8 1833.92  5151.1 1832.42  5200.0 1831.74  5224.3 1831.91
  5265.5 1833.76  5308.8 1833.45  5328.9 1832.61  5349.8 1829.41  5401.8 1832.45
  5412.6 1833.87  5445.0 1836.46  5505.3 1840.58  5510.6 1841.43  5534.4 1842.72
#Mann=3,-1,0
  4639.5    0.05       0  4975.3    0.05       0  4983.6    0.05       0
#XS Ineff=2,0
       0                 5073.10    0.00 1837.58
Permanent Ineff=
       F       F
Bank Sta=4975.3,4983.6
Exp/Cntr=0.3,0.1

Type RM Length L Ch R = 1,6141,182,182,182
BEGIN DESCRIPTION:
Mapping XS 07aebb77
END DESCRIPTION:
XS GIS Cut Line= 4
      1634987.58      6855185.12      1635321.66      6855085.89
      1635490.94      6855027.53      1635777.24      6854928.82
#Sta/Elev= 30
  4746.0 1840.00  4855.8 1835.24  4894.3 1834.33  4932.7 1832.40  4965.9 1829.90
  4972.8 1828.55  4994.9 1828.08  4995.4 1827.58  5003.3 1828.08  5014.5 1828.20
  5045.8 1832.53  5065.5 1832.17  5087.6 1833.55  5140.3 1833.36  5182.7 1830.66
  5235.5 1833.31  5267.3 1833.46  5299.0 1832.31  5321.8 1832.64  5353.0 1831.07
  5373.1 1828.24  5378.9 1830.12  5394.2 1831.00  5410.1 1830.44  5415.4 1828.48
  5447.1 1830.65  5467.3 1831.19  5478.8 1833.61  5503.7 1835.48  5576.4 1836.84
#Mann=3,-1,0
  4746.0    0.05       0  4994.9    0.03       0  5003.3    0.05       0
#XS Ineff=2,0
       0                 5088.20    0.00 1835.70
Permanent Ineff=
       F       F
Bank Sta=4994.9,5003.3
Exp/Cntr=0.3,0.1

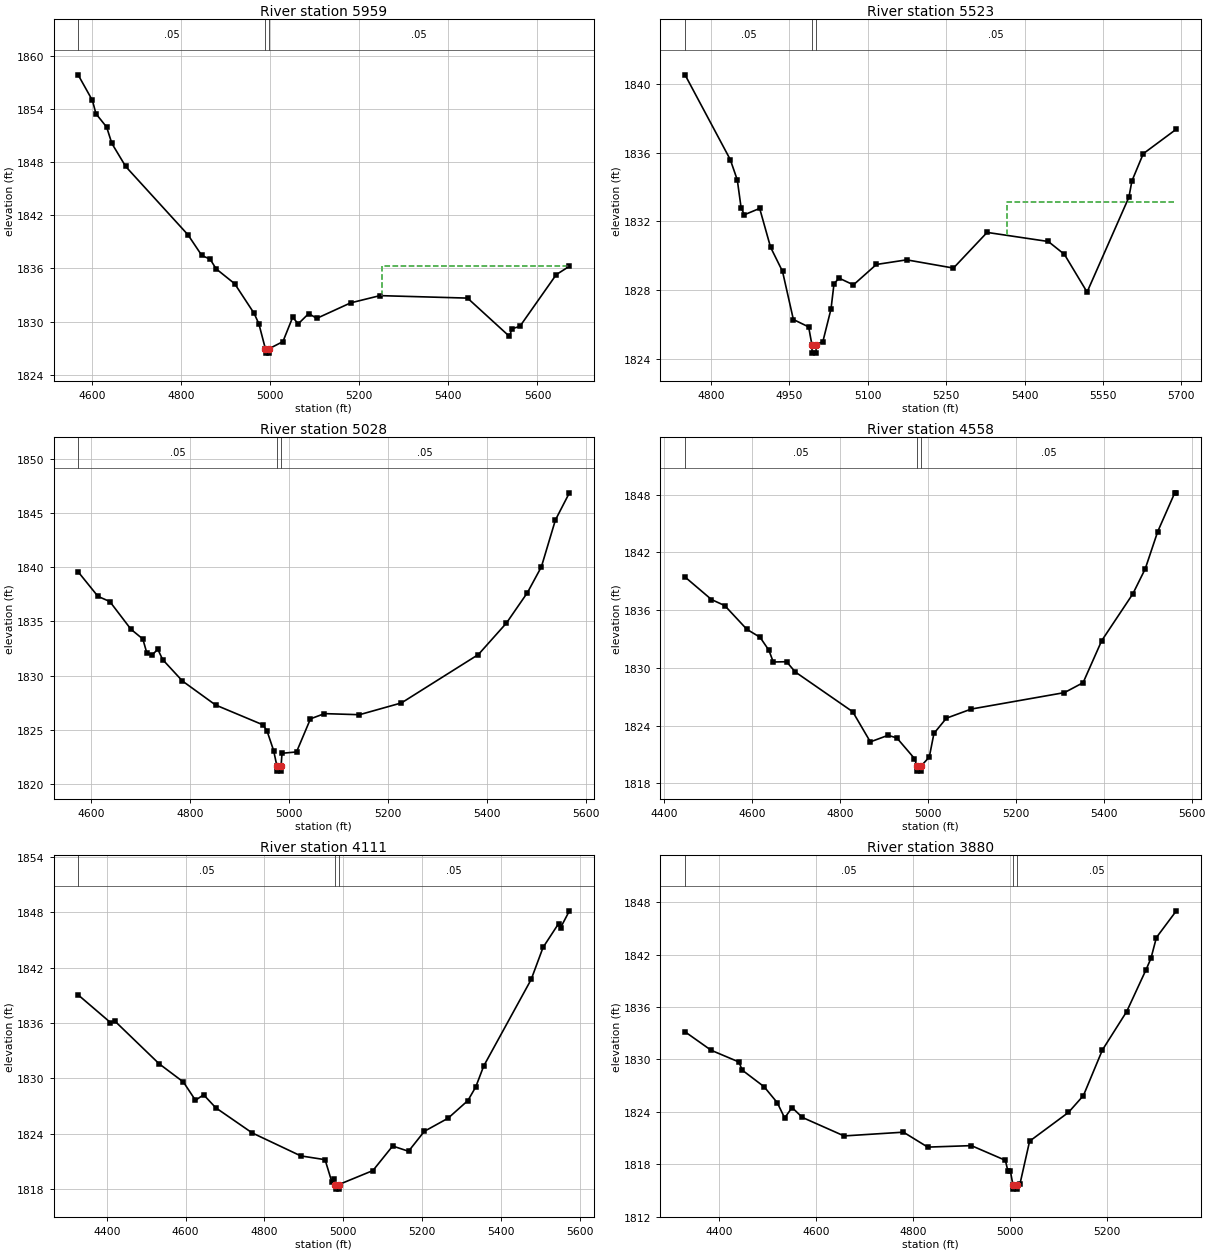
Type RM Length L Ch R = 1,5959,436,436,436
BEGIN DESCRIPTION:
Deadman 59 12.0
END DESCRIPTION:
XS GIS Cut Line= 4
      1634854.97      6855438.01      1635255.00      6855288.00
      1635574.35      6855150.41      1635875.61      6855020.62
#Sta/Elev= 30
  4568.7 1857.89  4600.8 1855.00  4608.8 1853.49  4632.8 1851.98  4644.4 1850.14
  4675.5 1847.53  4815.3 1839.81  4846.4 1837.47  4865.1 1837.05  4878.5 1835.96
  4920.3 1834.27  4963.9 1830.92  4974.6 1829.73  4989.1 1826.93  4989.6 1826.43
  4997.0 1826.43  4997.5 1826.93  5028.5 1827.73  5050.4 1830.48  5062.9 1829.74
  5086.4 1830.90  5104.5 1830.36  5180.5 1832.11  5246.4 1832.93  5443.0 1832.65
  5537.1 1828.32  5542.6 1829.18  5560.6 1829.46  5642.1 1835.30  5671.7 1836.25
#Mann=3,-1,0
  4568.7    0.05       0  4989.1    0.03       0  4997.5    0.05       0
#XS Ineff=2,0
       0                 5251.40    0.00 1836.27
Permanent Ineff=
       F       F
Bank Sta=4989.1,4997.5
Exp/Cntr=0.3,0.1

Type RM Length L Ch R = 1,5523,495,495,495
BEGIN DESCRIPTION:
Deadman 59 11.0
END DESCRIPTION:
XS GIS Cut Line= 4
      1635354.96      6855738.03      1635555.00      6855588.00
      1635751.43      6855254.58      1635905.27      6854993.45
#Sta/Elev= 30
  4750.4 1840.55  4836.9 1835.61  4850.4 1834.42  4857.7 1832.79  4864.0 1832.39
  4893.2 1832.76  4914.0 1830.50  4936.9 1829.09  4957.7 1826.28  4986.9 1825.85
  4993.1 1824.82  4993.6 1824.32  5001.0 1824.32  5001.5 1824.82  5014.1 1824.99
  5029.7 1826.89  5035.5 1828.38  5045.4 1828.69  5072.6 1828.30  5116.5 1829.49
  5174.5 1829.76  5264.0 1829.28  5328.4 1831.36  5445.5 1830.83  5476.3 1830.08
  5519.7 1827.88  5599.7 1833.41  5605.5 1834.36  5627.2 1835.95  5690.5 1837.38
#Mann=3,-1,0
  4750.4    0.05       0  4993.1    0.05       0  5001.5    0.05       0
#XS Ineff=2,0
       0                 5366.30    0.00 1833.16
Permanent Ineff=
       F       F
Bank Sta=4993.1,5001.5
Exp/Cntr=0.3,0.1

Type RM Length L Ch R = 1,5028,470,470,470
BEGIN DESCRIPTION:
Deadman 59 10.0
END DESCRIPTION:
XS GIS Cut Line= 3
      1635504.99      6856088.00      1635905.00      6855938.00
      1636305.00      6855538.00
#Sta/Elev= 30
  4574.3 1839.58  4614.4 1837.31  4638.4 1836.83  4681.1 1834.27  4705.1 1833.37
  4713.2 1832.08  4723.8 1831.90  4735.4 1832.42  4745.2 1831.47  4785.2 1829.49
  4852.0 1827.28  4948.1 1825.44  4956.1 1824.88  4969.5 1823.06  4975.9 1821.67
  4976.4 1821.17  4984.0 1821.17  4984.5 1821.67  4986.4 1822.82  5015.7 1822.94
  5043.9 1826.00  5072.2 1826.48  5142.9 1826.38  5227.8 1827.47  5383.3 1831.94
  5439.9 1834.84  5482.3 1837.65  5510.6 1840.04  5538.9 1844.36  5567.2 1846.87
#Mann=3,-1,0
  4574.3    0.05       0  4975.9    0.05       0  4984.5    0.05       0
Bank Sta=4975.9,4984.5
Exp/Cntr=0.3,0.1

Type RM Length L Ch R = 1,4558,447,447,447
BEGIN DESCRIPTION:
Deadman 59 9.0
END DESCRIPTION:
XS GIS Cut Line= 3
      1635555.00      6856388.00      1636105.00      6856338.00
      1636505.03      6855937.97
#Sta/Elev= 30
  4447.2 1839.43  4507.4 1837.09  4537.6 1836.46  4587.8 1834.00  4617.9 1833.17
  4638.0 1831.82  4648.0 1830.60  4678.1 1830.63  4698.2 1829.56  4828.8 1825.43
  4868.9 1822.30  4909.1 1822.98  4929.2 1822.71  4969.3 1820.57  4975.0 1819.76
  4975.5 1819.26  4983.2 1819.26  4983.7 1819.76  5003.0 1820.72  5013.6 1823.18
  5041.9 1824.76  5098.5 1825.71  5310.6 1827.42  5353.0 1828.45  5395.4 1832.82
  5466.2 1837.68  5494.4 1840.28  5522.7 1844.14  5561.6 1848.18  5565.2 1848.18
#Mann=3,-1,0
  4447.2    0.05       0  4975.0    0.05       0  4983.7    0.05       0
Bank Sta=4975,4983.7
Exp/Cntr=0.3,0.1

Type RM Length L Ch R = 1,4111,231,231,231
BEGIN DESCRIPTION:
Deadman 59 8.0
END DESCRIPTION:
XS GIS Cut Line= 3
      1635554.97      6856587.99      1636205.00      6856738.00
      1636781.59      6856691.12
#Sta/Elev= 30
  4327.5 1839.05  4409.6 1836.05  4419.9 1836.24  4532.8 1831.59  4594.4 1829.61
  4625.1 1827.63  4645.7 1828.23  4676.5 1826.82  4768.8 1824.10  4892.0 1821.61
  4953.6 1821.20  4970.7 1818.80  4975.8 1819.11  4979.9 1818.51  4980.4 1818.01
  4988.3 1818.01  4988.8 1818.51  5074.9 1820.02  5125.0 1822.68  5165.2 1822.11
  5205.3 1824.27  5265.5 1825.69  5315.7 1827.60  5335.7 1829.08  5355.8 1831.34
  5476.2 1840.72  5506.3 1844.19  5545.6 1846.76  5550.7 1846.32  5573.1 1848.15
#Mann=3,-1,0
  4327.5    0.05       0  4979.9    0.05       0  4988.8    0.05       0
Bank Sta=4979.9,4988.8
Exp/Cntr=0.3,0.1

Type RM Length L Ch R = 1,3880,333,333,333
BEGIN DESCRIPTION:
Mapping XS 4c69076b
END DESCRIPTION:
XS GIS Cut Line= 3
      1635685.42      6856733.72      1635966.71      6856910.83
      1636647.31      6856955.97
#Sta/Elev= 30
  4328.9 1833.16  4382.7 1831.05  4440.4 1829.70  4446.6 1828.79  4492.2 1826.87
  4519.3 1825.05  4534.6 1823.30  4549.9 1824.49  4571.1 1823.36  4657.3 1821.24
  4779.9 1821.67  4830.0 1819.96  4920.2 1820.13  4990.3 1818.45  4995.8 1817.18
  5000.8 1817.19  5005.9 1815.65  5006.4 1815.15  5014.3 1815.15  5014.8 1815.65
  5020.4 1815.72  5040.4 1820.64  5120.6 1823.93  5151.5 1825.86  5190.8 1831.09
  5240.9 1835.48  5281.0 1840.29  5291.0 1841.57  5302.2 1843.95  5343.4 1847.01
#Mann=3,-1,0
  4328.9    0.05       0  5005.9    0.05       0  5014.8    0.05       0
Bank Sta=5005.9,5014.8
Exp/Cntr=0.3,0.1

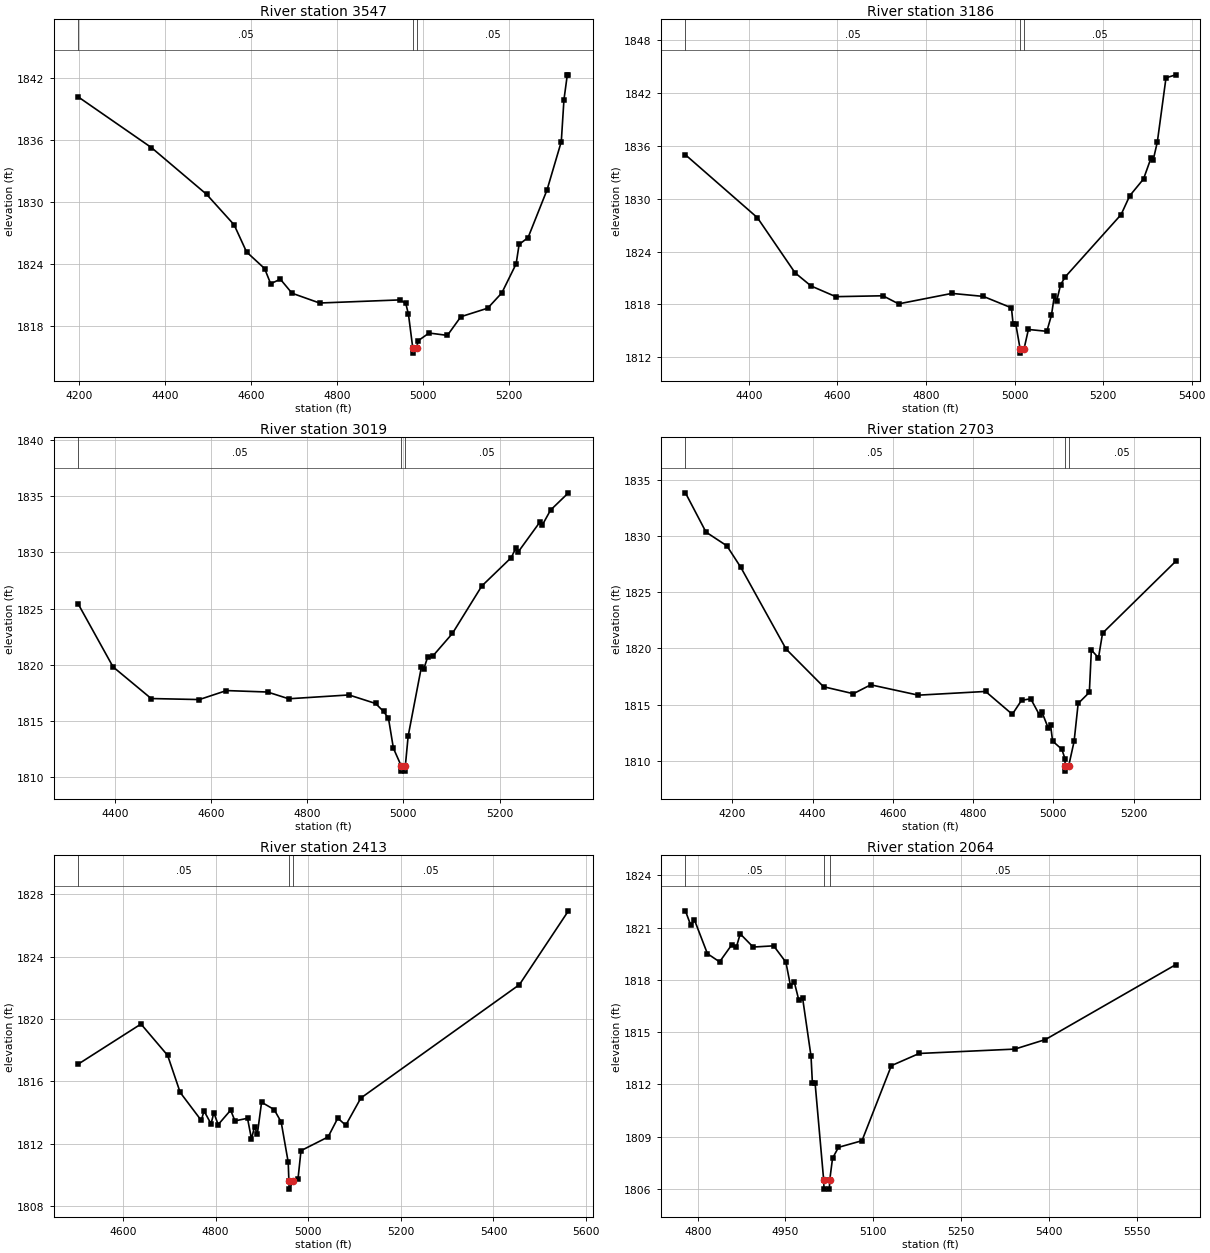
Type RM Length L Ch R = 1,3547,361,361,361
BEGIN DESCRIPTION:
Deadman 59 7.0
END DESCRIPTION:
XS GIS Cut Line= 3
      1635504.96      6856637.97      1636147.26      6857146.94
      1636454.96      6857237.99
#Sta/Elev= 30
  4197.8 1840.20  4368.5 1835.27  4496.7 1830.74  4560.8 1827.78  4589.7 1825.15
  4631.7 1823.54  4645.7 1822.07  4668.2 1822.51  4695.4 1821.15  4759.5 1820.20
  4945.4 1820.50  4959.8 1820.18  4966.2 1819.10  4976.2 1815.84  4976.7 1815.34
  4985.1 1815.84  4988.7 1816.54  5014.1 1817.29  5056.7 1817.06  5088.0 1818.87
  5150.5 1819.70  5183.3 1821.18  5216.6 1824.00  5223.5 1825.88  5244.4 1826.55
  5288.3 1831.15  5321.6 1835.85  5327.8 1839.92  5335.6 1842.33  5338.2 1842.33
#Mann=3,-1,0
  4197.8    0.05       0  4976.2    0.05       0  4985.1    0.05       0
Bank Sta=4976.2,4985.1
Exp/Cntr=0.3,0.1

Type RM Length L Ch R = 1,3186,167,167,167
BEGIN DESCRIPTION:
Deadman 59 6.0
END DESCRIPTION:
XS GIS Cut Line= 3
      1635555.01      6856938.01      1636105.00      6857438.00
      1636455.00      6857338.00
#Sta/Elev= 30
  4256.9 1835.00  4419.4 1827.85  4504.5 1821.58  4540.4 1820.09  4596.4 1818.87
  4702.9 1818.97  4738.3 1818.05  4858.6 1819.24  4929.6 1818.90  4993.1 1817.60
  4996.8 1815.78  5002.8 1815.78  5012.6 1812.95  5013.1 1812.45  5021.6 1812.95
  5031.4 1815.14  5073.0 1814.93  5083.4 1816.75  5089.9 1818.93  5095.1 1818.35
  5104.2 1820.24  5114.6 1821.12  5240.7 1828.20  5260.2 1830.34  5291.4 1832.25
  5308.3 1834.64  5313.5 1834.46  5322.6 1836.48  5342.1 1843.75  5364.2 1844.09
#Mann=3,-1,0
  4256.9    0.05       0  5012.6    0.05       0  5021.6    0.05       0
Bank Sta=5012.6,5021.6
Exp/Cntr=0.3,0.1

Type RM Length L Ch R = 1,3019,316,316,316
BEGIN DESCRIPTION:
Mapping XS ce539615
END DESCRIPTION:
XS GIS Cut Line= 3
      1635636.84      6857164.30      1635938.93      6857570.55
      1636441.23      6857674.48
#Sta/Elev= 30
  4323.8 1825.44  4396.5 1819.82  4475.8 1817.00  4575.9 1816.91  4632.2 1817.71
  4717.7 1817.58  4761.6 1816.98  4886.9 1817.32  4942.2 1816.56  4958.8 1815.85
  4969.0 1815.24  4979.2 1812.58  4995.1 1811.04  4995.6 1810.54  5003.6 1810.54
  5004.1 1811.04  5009.9 1813.66  5037.5 1819.83  5042.6 1819.67  5050.7 1820.72
  5060.9 1820.77  5101.8 1822.79  5163.0 1827.02  5224.3 1829.55  5233.2 1830.36
  5238.3 1830.03  5283.4 1832.69  5288.5 1832.43  5306.0 1833.78  5343.0 1835.31
#Mann=3,-1,0
  4323.8    0.05       0  4995.1    0.05       0  5004.1    0.05       0
Bank Sta=4995.1,5004.1
Exp/Cntr=0.3,0.1

Type RM Length L Ch R = 1,2703,290,290,290
BEGIN DESCRIPTION:
Deadman 59 5.0
END DESCRIPTION:
XS GIS Cut Line= 3
      1635505.00      6857038.01      1635955.00      6857838.00
      1636254.99      6857888.00
#Sta/Elev= 30
  4083.0 1833.82  4134.3 1830.33  4186.3 1829.11  4221.0 1827.20  4333.8 1819.94
  4427.2 1816.59  4501.5 1815.97  4544.8 1816.76  4663.4 1815.84  4831.0 1816.17
  4897.6 1814.14  4920.6 1815.38  4943.5 1815.52  4965.5 1814.07  4971.2 1814.36
  4987.2 1812.91  4992.9 1813.20  4998.0 1811.76  5021.1 1811.03  5028.7 1810.21
  5029.3 1809.59  5029.8 1809.09  5038.3 1809.59  5051.6 1811.73  5061.7 1815.10
  5089.6 1816.09  5094.6 1819.85  5112.4 1819.16  5122.5 1821.35  5305.0 1827.74
#Mann=3,-1,0
  4083.0    0.05       0  5029.3    0.05       0  5038.3    0.05       0
Bank Sta=5029.3,5038.3
Exp/Cntr=0.3,0.1

Type RM Length L Ch R = 1,2413,349,349,349
BEGIN DESCRIPTION:
Mapping XS 655c584d
END DESCRIPTION:
XS GIS Cut Line= 3
      1635404.23      6857452.53      1635669.71      6857867.40
      1636210.94      6858034.23
#Sta/Elev= 30
  4503.0 1817.10  4638.9 1819.68  4696.4 1817.67  4723.5 1815.29  4769.1 1813.49
  4775.0 1814.10  4790.2 1813.27  4796.2 1813.99  4805.5 1813.22  4832.5 1814.15
  4841.8 1813.46  4868.9 1813.63  4877.5 1812.30  4884.1 1813.09  4890.1 1812.61
  4899.3 1814.66  4926.4 1814.19  4941.6 1813.39  4956.8 1810.81  4958.3 1809.58
  4958.8 1809.08  4967.3 1809.58  4978.0 1809.75  4984.4 1811.55  5042.9 1812.43
  5063.9 1813.64  5081.0 1813.18  5113.7 1814.93  5456.1 1822.21  5561.9 1826.95
#Mann=3,-1,0
  4503.0    0.05       0  4958.3    0.03       0  4967.3    0.05       0
Bank Sta=4958.3,4967.3
Exp/Cntr=0.3,0.1

Type RM Length L Ch R = 1,2064,165,165,165
BEGIN DESCRIPTION:
Mapping XS b5021685
END DESCRIPTION:
XS GIS Cut Line= 3
      1635234.04      6857886.50      1635400.74      6858025.41
      1636018.83      6858084.44
#Sta/Elev= 30
  4779.0 1821.97  4788.0 1821.15  4794.5 1821.44  4816.6 1819.51  4837.4 1819.04
  4858.4 1820.03  4866.1 1819.89  4872.6 1820.65  4894.7 1819.89  4929.8 1819.96
  4950.7 1819.02  4958.5 1817.67  4965.0 1817.88  4972.8 1816.84  4979.3 1816.95
  4993.6 1813.63  4996.0 1812.07  5000.6 1812.07  5015.3 1806.49  5015.8 1805.99
  5025.0 1805.99  5025.5 1806.49  5030.4 1807.76  5040.5 1808.39  5080.7 1808.77
  5130.9 1813.08  5178.5 1813.78  5341.8 1814.03  5394.2 1814.58  5616.9 1818.88
#Mann=3,-1,0
  4779.0    0.05       0  5015.3    0.03       0  5025.5    0.05       0
Bank Sta=5015.3,5025.5
Exp/Cntr=0.3,0.1

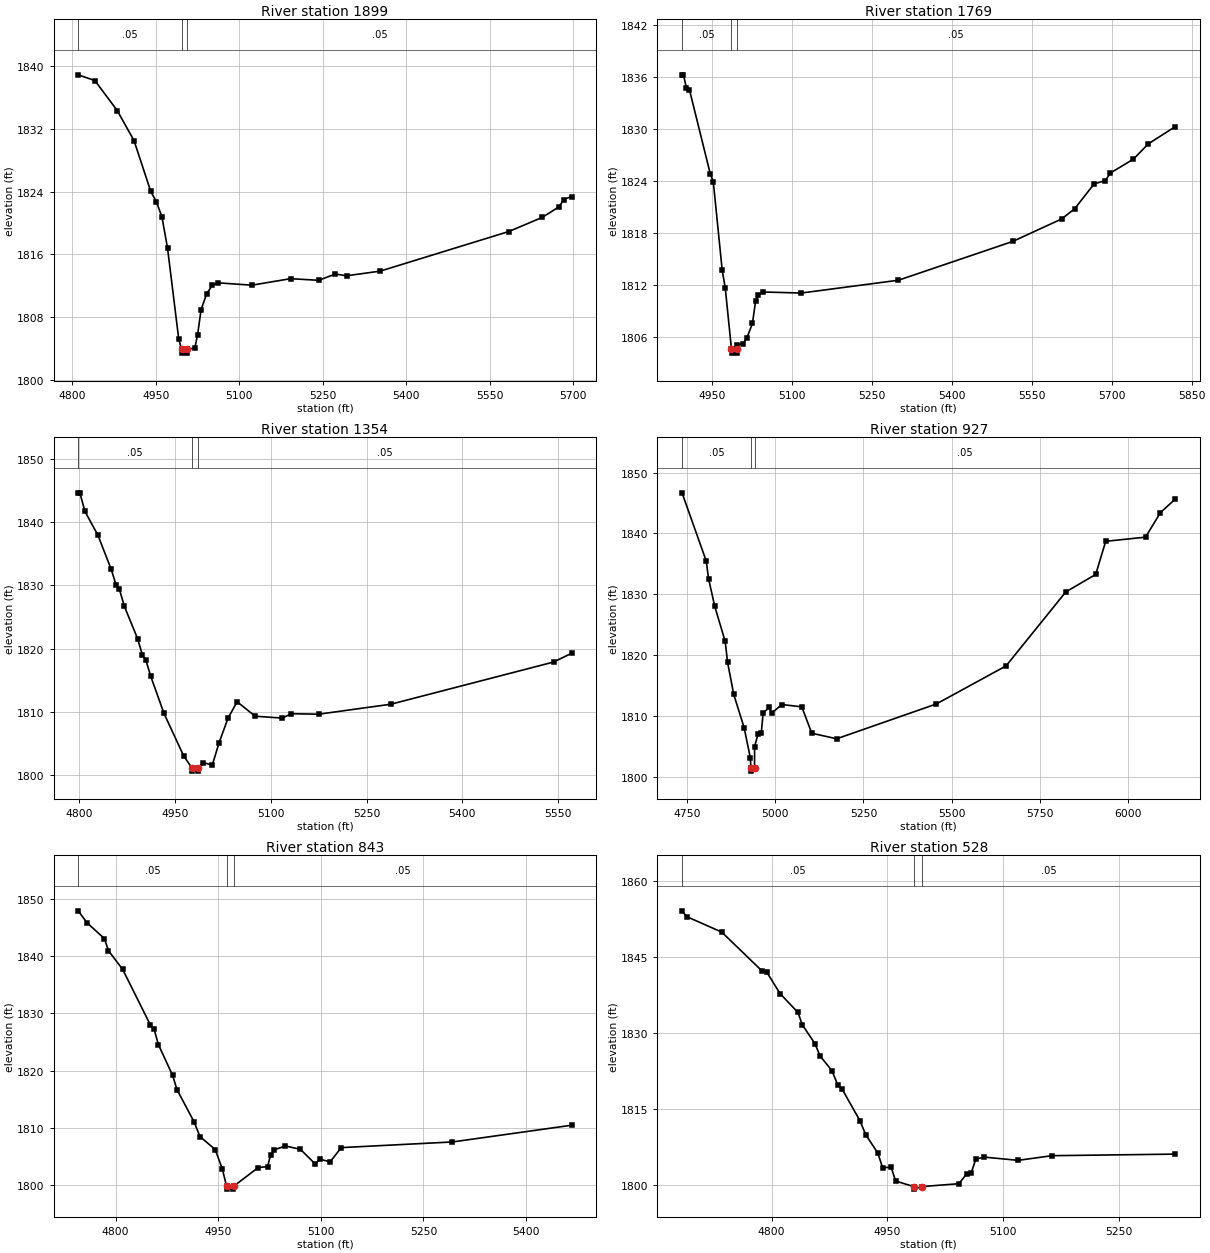
Type RM Length L Ch R = 1,1899,130,130,130
BEGIN DESCRIPTION:
Mapping XS f50a877a
END DESCRIPTION:
XS GIS Cut Line= 2
      1635265.31      6858195.55      1636147.24      6858101.81
#Sta/Elev= 30
  4810.5 1838.88  4840.4 1838.15  4880.6 1834.33  4910.8 1830.50  4940.9 1824.02
  4951.0 1822.71  4961.0 1820.77  4971.1 1816.77  4991.2 1805.20  4996.2 1803.91
  4996.7 1803.41  5005.9 1803.41  5006.4 1803.91  5020.1 1804.05  5025.1 1805.76
  5031.4 1808.97  5041.5 1810.99  5051.5 1812.05  5061.6 1812.37  5122.7 1812.07
  5192.3 1812.90  5242.6 1812.69  5272.8 1813.49  5292.9 1813.27  5353.2 1813.86
  5584.5 1818.91  5644.9 1820.72  5675.0 1822.07  5683.1 1822.99  5697.4 1823.37
#Mann=3,-1,0
  4810.5    0.05       0  4996.2    0.05       0  5006.4    0.05       0
Bank Sta=4996.2,5006.4
Exp/Cntr=0.3,0.1

Type RM Length L Ch R = 1,1769,415,415,415
BEGIN DESCRIPTION:
Deadman 59 4.0
END DESCRIPTION:
XS GIS Cut Line= 3
      1635405.04      6858337.98      1635505.00      6858288.00
      1636305.00      6858138.00
#Sta/Elev= 30
  4893.9 1836.26  4896.6 1836.26  4902.2 1834.73  4907.8 1834.54  4947.0 1824.80
  4952.5 1823.94  4969.3 1813.67  4974.9 1811.69  4986.6 1804.62  4987.1 1804.12
  4996.3 1804.12  4996.8 1804.62  4997.3 1805.08  5008.2 1805.22  5015.8 1805.92
  5026.0 1807.55  5031.9 1810.13  5037.0 1810.83  5046.4 1811.18  5117.6 1811.06
  5299.9 1812.54  5514.4 1817.02  5605.9 1819.61  5630.5 1820.79  5667.0 1823.66
  5688.2 1824.05  5697.5 1824.92  5740.7 1826.52  5768.7 1828.29  5819.6 1830.29
#Mann=3,-1,0
  4893.9    0.05       0  4986.6    0.05       0  4996.8    0.05       0
Bank Sta=4986.6,4996.8
Exp/Cntr=0.3,0.1

Type RM Length L Ch R = 1,1354,427,427,427
BEGIN DESCRIPTION:
Deadman 59 3.0
END DESCRIPTION:
XS GIS Cut Line= 3
      1635505.01      6858688.00      1635705.00      6858638.00
      1636104.98      6858238.02
#Sta/Elev= 30
  4799.0 1844.62  4801.6 1844.62  4809.3 1841.73  4829.9 1837.90  4850.5 1832.55
  4858.3 1830.04  4863.4 1829.38  4871.1 1826.69  4891.8 1821.58  4899.5 1818.95
  4904.6 1818.24  4912.4 1815.62  4933.0 1809.78  4963.9 1803.03  4976.9 1801.11
  4977.4 1800.61  4986.6 1800.61  4987.1 1801.11  4994.8 1801.94  5008.7 1801.57
  5019.3 1805.08  5033.4 1809.01  5047.6 1811.57  5075.9 1809.29  5118.3 1809.00
  5132.4 1809.69  5174.9 1809.61  5288.0 1811.19  5542.5 1817.86  5570.8 1819.25
#Mann=3,-1,0
  4799.0    0.05       0  4976.9    0.05       0  4987.1    0.05       0
Bank Sta=4976.9,4987.1
Exp/Cntr=0.3,0.1

Type RM Length L Ch R = 1,927,84,84,84
BEGIN DESCRIPTION:
Deadman 59 2.0
END DESCRIPTION:
XS GIS Cut Line= 3
      1635604.98      6859088.01      1635855.00      6858988.00
      1636655.03      6858187.97
#Sta/Elev= 30
  4734.9 1846.68  4803.6 1835.47  4810.3 1832.53  4827.8 1828.02  4857.4 1822.24
  4864.2 1818.81  4881.7 1813.53  4911.3 1808.04  4928.8 1803.09  4930.4 1801.42
  4930.9 1800.92  4940.7 1801.42  4940.9 1804.95  4950.3 1806.95  4959.8 1807.15
  4965.1 1810.48  4982.6 1811.41  4989.4 1810.45  5018.3 1811.87  5074.9 1811.49
  5103.2 1807.15  5173.9 1806.24  5456.7 1811.96  5654.7 1818.22  5824.4 1830.39
  5909.3 1833.26  5937.6 1838.71  6050.7 1839.39  6093.1 1843.44  6135.6 1845.67
#Mann=3,-1,0
  4734.9    0.05       0  4930.4    0.05       0  4940.7    0.05       0
Bank Sta=4930.4,4940.7
Exp/Cntr=0.3,0.1

Type RM Length L Ch R = 1,843,315,315,315
BEGIN DESCRIPTION:
Mapping XS 3158436d
END DESCRIPTION:
XS GIS Cut Line= 3
      1635612.56      6859143.46      1635876.43      6859067.08
      1636267.70      6858852.40
#Sta/Elev= 30
  4745.5 1847.89  4758.4 1845.80  4783.8 1843.04  4789.7 1840.93  4810.5 1837.65
  4851.0 1827.95  4856.2 1827.32  4862.6 1824.54  4883.4 1819.16  4889.8 1816.67
  4914.6 1811.08  4923.4 1808.47  4945.8 1806.18  4956.2 1802.74  4962.3 1799.78
  4962.8 1799.28  4972.1 1799.28  4972.6 1799.78  5008.3 1803.03  5022.2 1803.23
  5026.5 1805.19  5032.2 1806.16  5048.3 1806.81  5070.1 1806.24  5091.9 1803.67
  5098.4 1804.51  5113.7 1804.05  5129.8 1806.53  5292.3 1807.52  5466.5 1810.44
#Mann=3,-1,0
  4745.5    0.05       0  4962.3    0.05       0  4972.6    0.05       0
Bank Sta=4962.3,4972.6
Exp/Cntr=0.3,0.1

Type RM Length L Ch R = 1,528,343,343,343
BEGIN DESCRIPTION:
Mapping XS 51e3e9e6
END DESCRIPTION:
XS GIS Cut Line= 2
      1635668.10      6859487.22      1636250.76      6859223.63
#Sta/Elev= 30
  4684.0 1854.02  4690.2 1852.87  4735.5 1849.82  4788.1 1842.09  4793.6 1841.97
  4811.2 1837.66  4834.3 1833.96  4839.8 1831.55  4856.2 1827.83  4862.9 1825.37
  4878.2 1822.51  4886.0 1819.61  4891.5 1818.83  4914.6 1812.60  4922.1 1809.83
  4937.7 1806.23  4944.0 1803.33  4955.0 1803.43  4960.8 1800.71  4984.2 1799.60
  4984.7 1799.10  4994.5 1799.60  5042.8 1800.17  5053.2 1802.15  5058.7 1802.26
  5064.7 1805.01  5075.7 1805.42  5119.6 1804.78  5163.5 1805.70  5323.5 1806.01
#Mann=3,-1,0
  4684.0    0.05       0  4984.2    0.05       0  4994.5    0.05       0
Bank Sta=4984.2,4994.5
Exp/Cntr=0.3,0.1

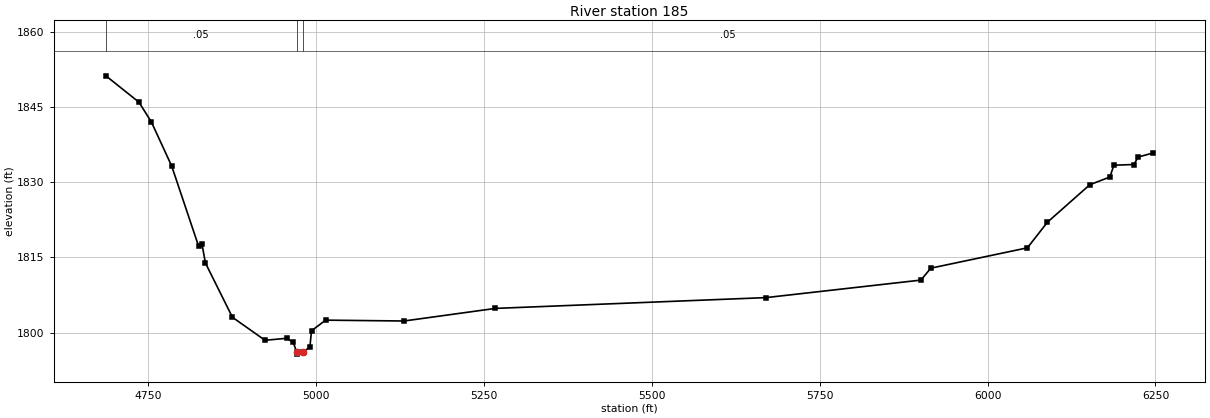
Type RM Length L Ch R = 1,185,0,0,0
BEGIN DESCRIPTION:
Deadman 59 1.0
END DESCRIPTION:
XS GIS Cut Line= 3
      1635747.56      6859707.70      1636049.63      6859676.46
      1636754.98      6858638.04
#Sta/Elev= 30
  4687.4 1851.17  4736.6 1845.92  4755.2 1841.95  4785.4 1833.18  4825.4 1817.23
  4830.4 1817.68  4835.6 1813.87  4875.8 1803.06  4924.3 1798.48  4956.3 1798.87
  4966.3 1798.08  4971.2 1796.22  4971.7 1795.72  4981.5 1796.22  4991.1 1797.11
  4993.5 1800.37  5014.5 1802.49  5131.2 1802.32  5267.3 1804.83  5670.1 1806.98
  5900.7 1810.47  5915.6 1812.85  6059.3 1816.90  6089.2 1822.01  6152.2 1829.47
  6182.1 1831.01  6188.1 1833.36  6218.0 1833.50  6224.0 1834.98  6246.4 1835.80
#Mann=3,-1,0
  4687.4    0.05       0  4971.2    0.03       0  4981.5    0.05       0
Bank Sta=4971.2,4981.5
Exp/Cntr=0.3,0.1