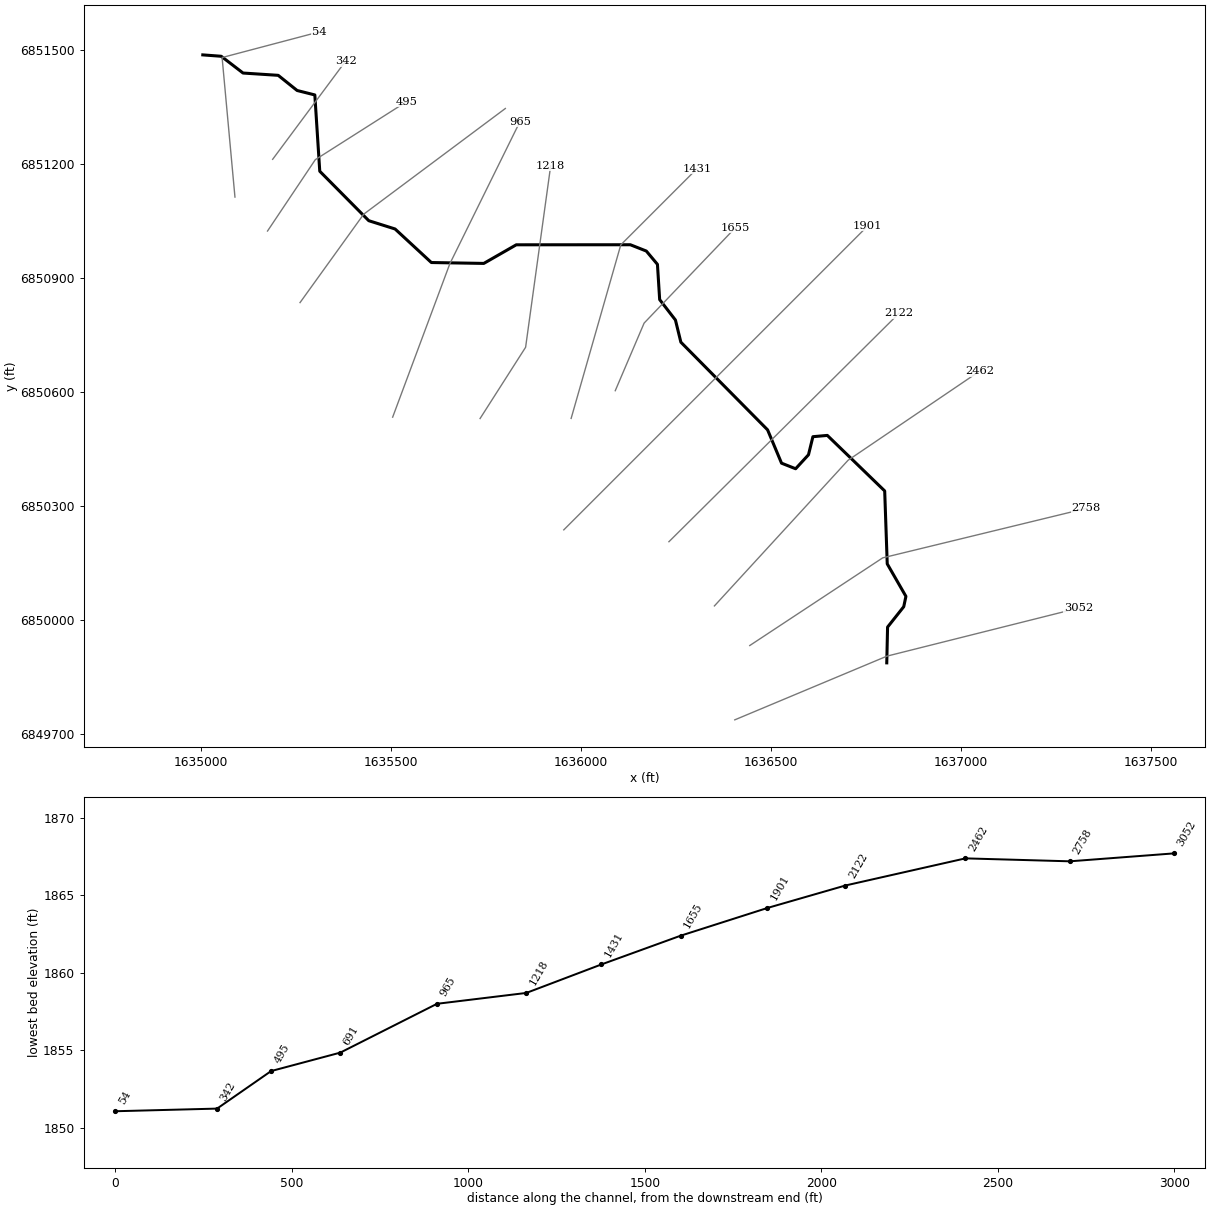
--- Deadman 60.prj (project) ---

Proj Title=Deadman 60 Base Level Engineering
Current Plan=p01
Default Exp/Contr=0.3,0.1
English Units
Geom File=g01
Flow File=f01
Plan File=p01
BEGIN DESCRIPTION:
Deadman 60
END DESCRIPTION:

--- Deadman 60.p01 (plan) ---

Plan Title=Multiple Run
Short Identifier=Multiple
Geom File=g01
Flow File=f01
Subcritical Flow
K Sum by GR= 0
Std Step Tol= 0.01
Critical Tol= 0.01
Num of Std Step Trials= 20
Max Error Tol= 0.3
Flow Tol Ratio= 0.001
Split Flow NTrial= 30
Split Flow Tol= 0.02
Split Flow Ratio= 0.02
Log Output Level= 0
Friction Slope Method= 1
Unsteady Friction Slope Method= 2
Unsteady Bridges Friction Slope Method= 1
Parabolic Critical Depth
Global Vel Dist=  1 , 1 , 1
Global Log Level= 0
CheckData=True
Encroach Param= -1, 0, 0, 0
BEGIN DESCRIPTION:
Multiple Run
END DESCRIPTION:

--- Deadman 60.f01 (steady flow) ---

Flow Title=Multiple
Number of Profiles=7
Profile Names=10-year,25-year,50-year,1pct_min,100-year,1pct_plu,500-year
River Rch & RM= Deadman 60,Reach-1,3052
     227     310     378     229     458     913     680
River Rch & RM= Deadman 60,Reach-1,2758
     239     329     404     246     491     981     739
Boundary for River Rch & Prof#=Deadman 60,Reach-1,1
Up Type=0
Dn Type=3
Dn Slope=0.007
Boundary for River Rch & Prof#=Deadman 60,Reach-1,2
Up Type=0
Dn Type=3
Dn Slope=0.007
Boundary for River Rch & Prof#=Deadman 60,Reach-1,3
Up Type=0
Dn Type=3
Dn Slope=0.007
Boundary for River Rch & Prof#=Deadman 60,Reach-1,4
Up Type=0
Dn Type=3
Dn Slope=0.007
Boundary for River Rch & Prof#=Deadman 60,Reach-1,5
Up Type=0
Dn Type=3
Dn Slope=0.007
Boundary for River Rch & Prof#=Deadman 60,Reach-1,6
Up Type=0
Dn Type=3
Dn Slope=0.007
Boundary for River Rch & Prof#=Deadman 60,Reach-1,7
Up Type=0
Dn Type=3
Dn Slope=0.007

--- Deadman 60.g01 (geometry) ---

Geom Title=Existing Conditions

River Reach=Deadman 60,Reach-1
Reach XY= 30
      1636805.00      6849888.00      1636807.13      6849982.14
      1636849.67      6850035.81      1636855.42      6850063.00
      1636806.24      6850148.50      1636799.54      6850340.45
      1636648.57      6850486.57      1636610.62      6850483.19
      1636598.99      6850435.59      1636565.17      6850398.83
      1636528.06      6850413.52      1636491.37      6850501.18
      1636263.14      6850731.94      1636248.86      6850790.17
      1636207.34      6850843.97      1636201.49      6850936.75
      1636172.22      6850971.76      1636130.22      6850988.33
      1635829.92      6850988.20      1635744.49      6850939.21
      1635606.47      6850941.54      1635511.04      6851029.82
      1635441.79      6851051.63      1635312.81      6851181.81
      1635299.83      6851382.59      1635253.22      6851394.30
      1635203.45      6851434.19      1635110.92      6851440.23
      1635053.49      6851484.36      1635005.00      6851488.00

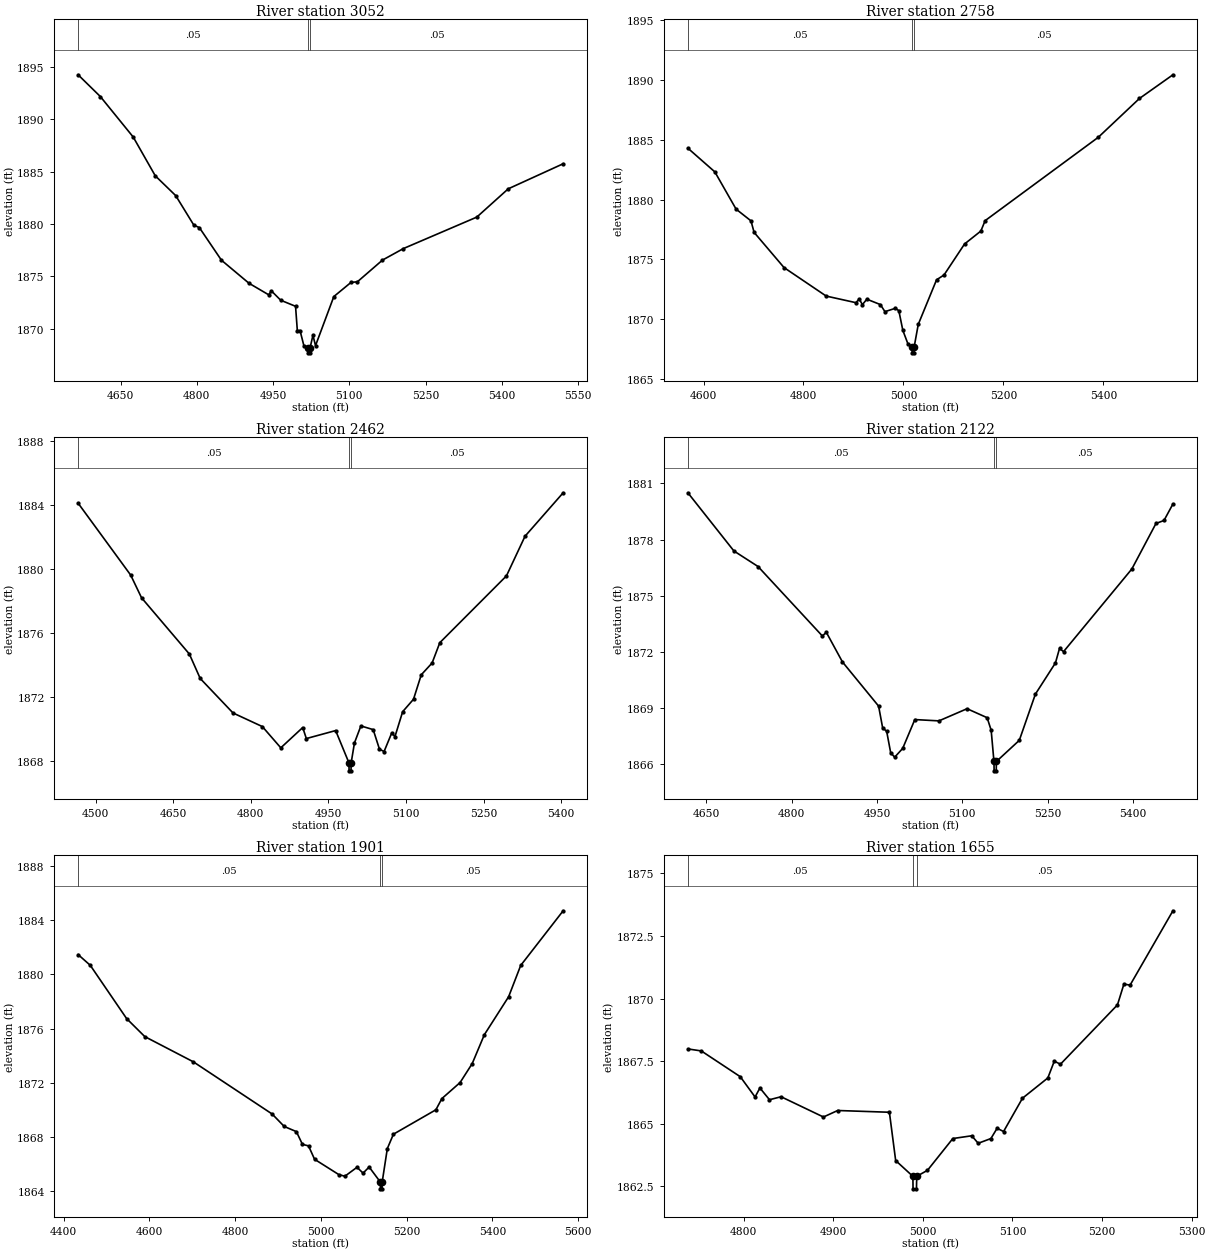
Type RM Length L Ch R = 1,3052,294,294,294
BEGIN DESCRIPTION:
Deadman 60 5.0
END DESCRIPTION:
XS GIS Cut Line= 3
      1636404.98      6849737.99      1636805.45      6849905.67
      1637309.76      6850032.21
#Sta/Elev= 30
  4566.5 1894.24  4610.3 1892.16  4674.9 1888.30  4718.3 1884.60  4758.5 1882.71
  4794.2 1879.89  4805.0 1879.66  4848.4 1876.55  4902.6 1874.35  4941.3 1873.25
  4946.7 1873.62  4965.0 1872.73  4994.2 1872.15  4997.7 1869.84  5003.0 1869.84
  5010.5 1868.41  5018.7 1868.21  5019.0 1867.71  5022.6 1867.71  5022.9 1868.21
  5028.4 1869.38  5033.5 1868.40  5069.5 1873.08  5103.3 1874.43  5115.9 1874.49
  5165.2 1876.56  5206.4 1877.66  5350.7 1880.66  5412.6 1883.36  5520.6 1885.75
#Mann=3,-1,0
  4566.5    0.05       0  5018.7    0.03       0  5022.9    0.05       0
Bank Sta=5018.7,5022.9
Exp/Cntr=0.3,0.1

Type RM Length L Ch R = 1,2758,296,296,296
BEGIN DESCRIPTION:
Mapping XS fb13b349
END DESCRIPTION:
XS GIS Cut Line= 3
      1636444.43      6849933.57      1636794.29      6850164.33
      1637330.08      6850294.56
#Sta/Elev= 30
  4568.7 1884.29  4622.7 1882.31  4665.2 1879.20  4695.0 1878.22  4701.2 1877.26
  4761.1 1874.32  4845.5 1871.94  4904.8 1871.39  4911.8 1871.70  4917.8 1871.22
  4926.8 1871.68  4953.9 1871.23  4963.0 1870.64  4984.0 1870.92  4990.8 1870.72
  4998.8 1869.08  5009.1 1867.94  5017.3 1867.70  5017.5 1867.20  5021.2 1867.20
  5021.5 1867.70  5029.7 1869.58  5066.3 1873.30  5081.2 1873.70  5122.3 1876.29
  5154.9 1877.37  5163.5 1878.24  5389.9 1885.20  5472.2 1888.44  5539.2 1890.42
#Mann=3,-1,0
  4568.7    0.05       0  5017.3    0.05       0  5021.5    0.05       0
Bank Sta=5017.3,5021.5
Exp/Cntr=0.3,0.1

Type RM Length L Ch R = 1,2462,340,340,340
BEGIN DESCRIPTION:
Mapping XS 79b57fb7
END DESCRIPTION:
XS GIS Cut Line= 3
      1636351.43      6850037.82      1636703.11      6850421.13
      1637049.26      6850655.62
#Sta/Elev= 30
  4465.8 1884.14  4567.5 1879.64  4588.5 1878.22  4681.0 1874.70  4702.0 1873.17
  4765.5 1871.01  4822.2 1870.16  4857.9 1868.83  4900.3 1870.10  4907.3 1869.41
  4964.0 1869.91  4989.7 1867.89  4990.0 1867.39  4993.7 1867.39  4994.0 1867.89
  5000.4 1869.14  5012.8 1870.20  5036.6 1869.97  5048.8 1868.74  5057.7 1868.60
  5072.6 1869.77  5078.7 1869.53  5093.6 1871.09  5114.6 1871.87  5129.6 1873.40
  5150.6 1874.14  5165.5 1875.41  5294.4 1879.59  5330.3 1882.07  5404.1 1884.79
#Mann=3,-1,0
  4465.8    0.05       0  4989.7    0.05       0  4994.0    0.05       0
Bank Sta=4989.7,4994
Exp/Cntr=0.3,0.1

Type RM Length L Ch R = 1,2122,221,221,221
BEGIN DESCRIPTION:
Mapping XS 245e1d76
END DESCRIPTION:
XS GIS Cut Line= 2
      1636231.71      6850206.80      1636837.18      6850807.93
#Sta/Elev= 30
  4617.3 1880.50  4698.3 1877.39  4740.7 1876.56  4853.8 1872.85  4860.9 1873.04
  4889.2 1871.46  4952.8 1869.10  4959.9 1867.94  4967.0 1867.75  4974.1 1866.60
  4981.1 1866.37  4995.2 1866.84  5016.5 1868.38  5058.9 1868.31  5108.4 1868.96
  5143.7 1868.48  5150.8 1867.81  5155.7 1866.14  5156.0 1865.64  5159.7 1865.64
  5160.0 1866.14  5200.3 1867.27  5228.6 1869.74  5263.9 1871.41  5271.0 1872.18
  5278.1 1872.01  5398.3 1876.43  5440.7 1878.86  5454.8 1879.02  5470.5 1879.90
#Mann=3,-1,0
  4617.3    0.05       0  5155.7    0.03       0  5160.0    0.05       0
Bank Sta=5155.7,5160
Exp/Cntr=0.3,0.1

Type RM Length L Ch R = 1,1901,246,246,246
BEGIN DESCRIPTION:
Deadman 60 4.0
END DESCRIPTION:
XS GIS Cut Line= 3
      1635955.02      6850238.02      1636355.00      6850638.00
      1636754.97      6851037.97
#Sta/Elev= 30
  4433.6 1881.47  4461.9 1880.68  4546.7 1876.75  4589.1 1875.42  4702.3 1873.56
  4886.1 1869.71  4914.4 1868.79  4942.7 1868.41  4956.8 1867.47  4971.0 1867.36
  4985.1 1866.37  5041.7 1865.24  5055.8 1865.12  5084.1 1865.78  5098.2 1865.35
  5112.4 1865.80  5138.5 1864.69  5138.8 1864.19  5142.5 1864.19  5142.8 1864.69
  5154.8 1867.16  5169.0 1868.22  5268.0 1870.02  5282.1 1870.85  5324.5 1872.03
  5352.8 1873.43  5381.1 1875.56  5437.7 1878.36  5465.9 1880.67  5564.9 1884.70
#Mann=3,-1,0
  4433.6    0.05       0  5138.5    0.03       0  5142.8    0.05       0
Bank Sta=5138.5,5142.8
Exp/Cntr=0.3,0.1

Type RM Length L Ch R = 1,1655,224,224,224
BEGIN DESCRIPTION:
Mapping XS f884e4bc
END DESCRIPTION:
XS GIS Cut Line= 3
      1636090.48      6850604.23      1636166.42      6850782.15
      1636406.91      6851033.47
#Sta/Elev= 30
  4737.8 1867.99  4752.8 1867.91  4796.3 1866.88  4812.8 1866.07  4818.2 1866.43
  4828.9 1865.96  4841.8 1866.08  4889.1 1865.27  4905.0 1865.53  4962.7 1865.46
  4969.7 1863.53  4988.9 1862.90  4989.1 1862.40  4992.9 1862.40  4993.2 1862.90
  5005.2 1863.14  5033.5 1864.41  5054.6 1864.52  5061.8 1864.22  5076.0 1864.41
  5082.9 1864.82  5090.1 1864.69  5111.2 1866.02  5139.5 1866.83  5146.7 1867.50
  5153.6 1867.38  5217.2 1869.75  5224.4 1870.58  5231.3 1870.54  5279.1 1873.51
#Mann=3,-1,0
  4737.8    0.05       0  4988.9    0.03       0  4993.2    0.05       0
Bank Sta=4988.9,4993.2
Exp/Cntr=0.3,0.1

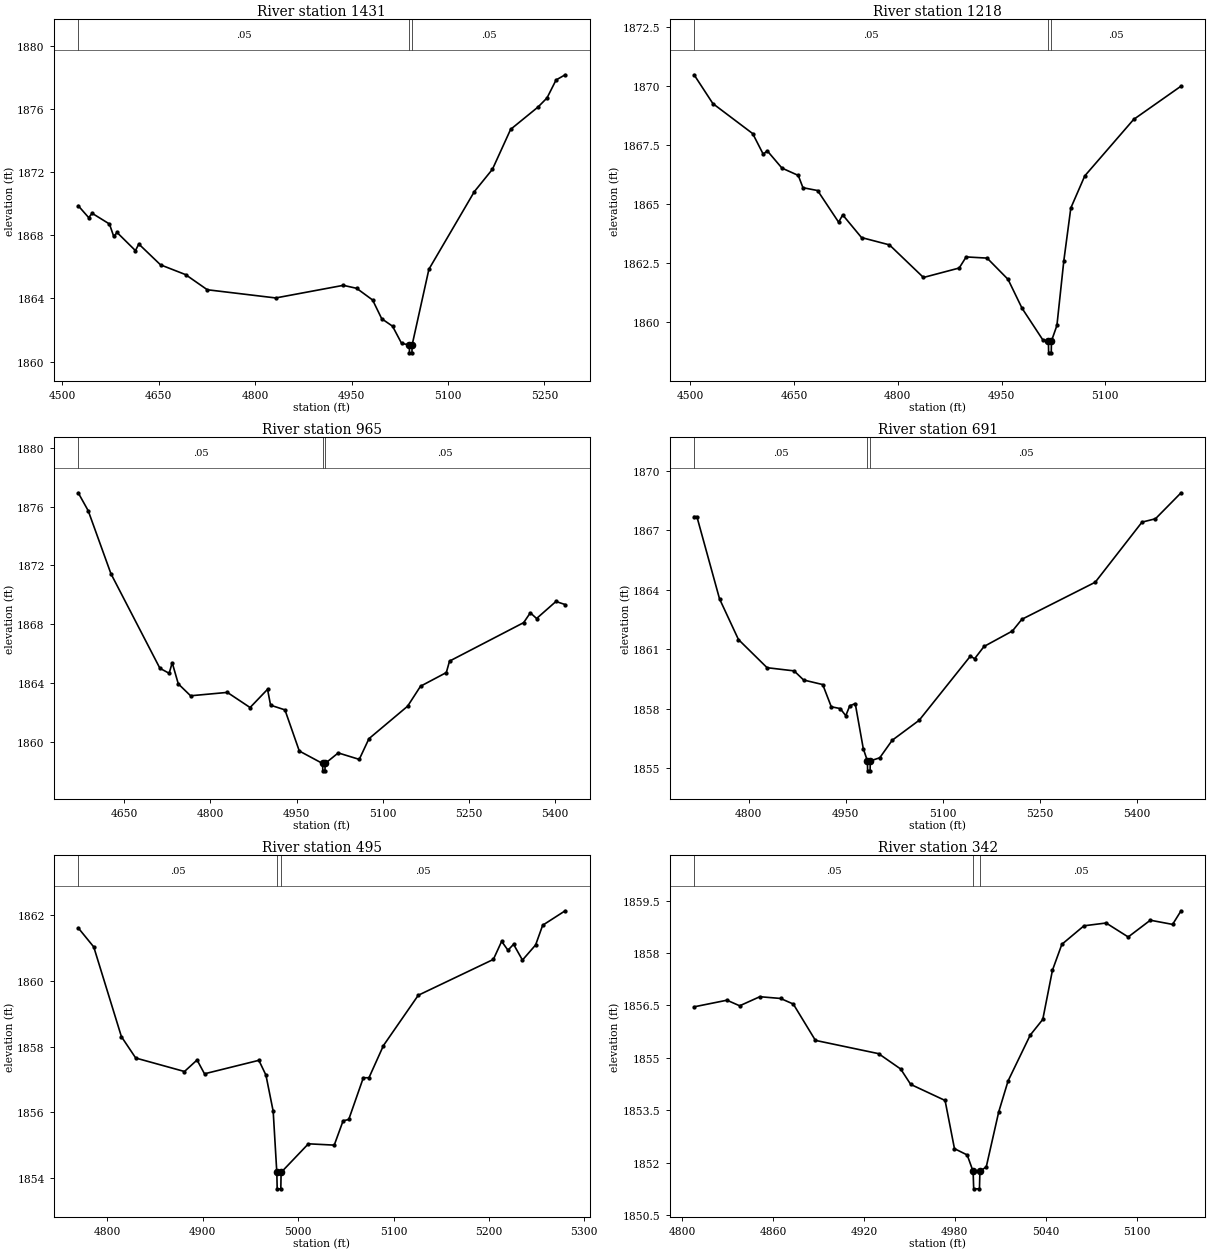
Type RM Length L Ch R = 1,1431,213,213,213
BEGIN DESCRIPTION:
Deadman 60 3.0
END DESCRIPTION:
XS GIS Cut Line= 3
      1635974.36      6850531.27      1636105.00      6850988.00
      1636305.01      6851188.01
#Sta/Elev= 30
  4524.5 1869.88  4540.9 1869.12  4546.1 1869.40  4573.1 1868.72  4579.8 1867.93
  4585.0 1868.18  4613.6 1867.03  4618.8 1867.45  4652.6 1866.13  4691.6 1865.51
  4725.4 1864.55  4831.9 1864.03  4937.1 1864.83  4957.9 1864.64  4982.7 1863.90
  4996.9 1862.71  5013.7 1862.24  5027.8 1861.15  5039.8 1861.05  5040.1 1860.55
  5043.9 1860.55  5044.2 1861.05  5070.3 1865.85  5141.0 1870.77  5169.2 1872.19
  5197.5 1874.72  5240.0 1876.13  5254.1 1876.71  5268.2 1877.85  5282.4 1878.18
#Mann=3,-1,0
  4524.5    0.05       0  5039.8    0.05       0  5044.2    0.05       0
Bank Sta=5039.8,5044.2
Exp/Cntr=0.3,0.1

Type RM Length L Ch R = 1,1218,253,253,253
BEGIN DESCRIPTION:
Mapping XS db4624f8
END DESCRIPTION:
XS GIS Cut Line= 3
      1635734.73      6850530.99      1635854.53      6850718.50
      1635920.50      6851195.96
#Sta/Elev= 30
  4505.2 1870.48  4532.4 1869.26  4590.0 1867.99  4605.2 1867.12  4611.1 1867.26
  4632.3 1866.53  4655.9 1866.22  4662.7 1865.70  4683.9 1865.58  4714.3 1864.24
  4720.2 1864.55  4747.4 1863.59  4787.8 1863.28  4837.0 1861.90  4888.7 1862.30
  4898.8 1862.77  4929.1 1862.72  4959.4 1861.82  4979.6 1860.60  5009.9 1859.25
  5017.8 1859.21  5018.1 1858.71  5021.9 1858.71  5022.2 1859.21  5030.1 1859.87
  5040.1 1862.61  5050.2 1864.84  5070.4 1866.20  5141.1 1868.59  5209.7 1870.00
#Mann=3,-1,0
  4505.2    0.05       0  5017.8    0.05       0  5022.2    0.05       0
Bank Sta=5017.8,5022.2
Exp/Cntr=0.3,0.1

Type RM Length L Ch R = 1,965,274,274,274
BEGIN DESCRIPTION:
Deadman 60 2.0
END DESCRIPTION:
XS GIS Cut Line= 3
      1635504.69      6850534.63      1635655.00      6850938.00
      1635839.65      6851312.48
#Sta/Elev= 30
  4569.7 1876.94  4587.1 1875.72  4626.7 1871.43  4712.0 1864.99  4728.1 1864.65
  4733.4 1865.37  4744.0 1863.93  4765.4 1863.12  4829.4 1863.35  4869.0 1862.32
  4899.4 1863.56  4904.7 1862.48  4929.7 1862.16  4954.7 1859.36  4995.3 1858.51
  4995.6 1858.01  4999.4 1858.01  4999.7 1858.51  5022.5 1859.23  5059.1 1858.79
  5076.0 1860.20  5143.3 1862.41  5165.8 1863.77  5210.7 1864.70  5216.3 1865.48
  5345.4 1868.10  5357.0 1868.77  5367.9 1868.38  5401.6 1869.54  5417.7 1869.33
#Mann=3,-1,0
  4569.7    0.05       0  4995.3    0.05       0  4999.7    0.05       0
Bank Sta=4995.3,4999.7
Exp/Cntr=0.3,0.1

Type RM Length L Ch R = 1,691,196,196,196
BEGIN DESCRIPTION:
Mapping XS da32a7c3
END DESCRIPTION:
XS GIS Cut Line= 3
      1635260.91      6850836.09      1635428.40      6851068.72
      1635801.19      6851346.92
#Sta/Elev= 30
  4715.9 1867.68  4720.2 1867.68  4755.2 1863.53  4784.4 1861.48  4828.6 1860.06
  4870.3 1859.90  4885.0 1859.44  4914.5 1859.21  4927.7 1858.09  4941.5 1858.00
  4950.1 1857.64  4956.2 1858.14  4964.7 1858.25  4977.1 1855.98  4983.5 1855.36
  4983.8 1854.86  4987.6 1854.86  4987.9 1855.36  5002.6 1855.52  5021.7 1856.40
  5063.4 1857.41  5142.6 1860.65  5148.9 1860.51  5163.5 1861.13  5207.3 1861.91
  5221.9 1862.50  5335.2 1864.37  5407.4 1867.40  5428.2 1867.57  5467.7 1868.88
#Mann=3,-1,0
  4715.9    0.05       0  4983.5    0.03       0  4987.9    0.05       0
Bank Sta=4983.5,4987.9
Exp/Cntr=0.3,0.1

Type RM Length L Ch R = 1,495,153,153,153
BEGIN DESCRIPTION:
Mapping XS 1641af45
END DESCRIPTION:
XS GIS Cut Line= 3
      1635175.35      6851024.46      1635301.13      6851212.26
      1635541.20      6851364.88
#Sta/Elev= 30
  4769.4 1861.61  4785.7 1861.03  4814.7 1858.30  4829.7 1857.65  4880.8 1857.24
  4894.0 1857.59  4901.8 1857.17  4958.8 1857.58  4966.2 1857.13  4973.8 1856.03
  4977.6 1854.17  4978.0 1853.67  4981.8 1853.67  4982.1 1854.17  5010.7 1855.04
  5037.8 1855.00  5047.1 1855.74  5053.0 1855.78  5068.3 1857.05  5074.2 1857.05
  5089.4 1858.03  5125.9 1859.56  5204.6 1860.65  5213.3 1861.20  5219.9 1860.93
  5225.8 1861.11  5235.1 1860.63  5248.9 1861.09  5256.3 1861.69  5279.9 1862.13
#Mann=3,-1,0
  4769.4    0.05       0  4977.6    0.03       0  4982.1    0.05       0
Bank Sta=4977.6,4982.1
Exp/Cntr=0.3,0.1

Type RM Length L Ch R = 1,342,288,288,288
BEGIN DESCRIPTION:
Mapping XS b289b46e
END DESCRIPTION:
XS GIS Cut Line= 2
      1635188.85      6851213.20      1635380.60      6851471.25
#Sta/Elev= 30
  4807.9 1856.46  4829.6 1856.65  4838.0 1856.49  4851.3 1856.75  4865.0 1856.70
  4873.4 1856.54  4888.0 1855.50  4929.7 1855.12  4944.3 1854.68  4950.9 1854.24
  4973.6 1853.78  4979.8 1852.40  4988.2 1852.22  4992.1 1851.75  4992.5 1851.25
  4996.3 1851.25  4996.6 1851.75  5000.8 1851.88  5009.0 1853.45  5015.2 1854.34
  5029.8 1855.65  5038.1 1856.10  5044.5 1857.51  5050.7 1858.25  5065.3 1858.78
  5079.9 1858.86  5094.5 1858.46  5109.1 1858.94  5123.8 1858.82  5129.4 1859.21
#Mann=3,-1,0
  4807.9    0.05       0  4992.1    0.03       0  4996.6    0.05       0
Bank Sta=4992.1,4996.6
Exp/Cntr=0.3,0.1

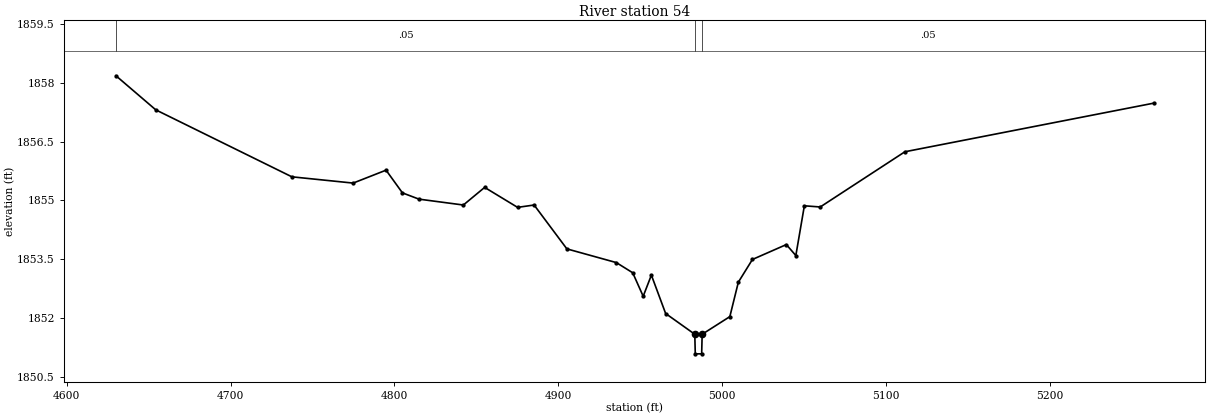
Type RM Length L Ch R = 1,54,0,0,0
BEGIN DESCRIPTION:
Deadman 60 1.0
END DESCRIPTION:
XS GIS Cut Line= 3
      1635089.63      6851113.81      1635055.82      6851481.01
      1635311.80      6851548.61
#Sta/Elev= 30
  4630.0 1858.18  4654.3 1857.31  4737.4 1855.60  4774.8 1855.44  4794.9 1855.77
  4804.9 1855.19  4815.0 1855.03  4842.1 1854.88  4855.1 1855.33  4875.2 1854.82
  4885.3 1854.88  4905.3 1853.76  4935.5 1853.41  4945.5 1853.15  4951.9 1852.55
  4956.9 1853.09  4965.6 1852.11  4983.4 1851.58  4983.7 1851.08  4987.6 1851.08
  4987.9 1851.58  5004.8 1852.03  5010.0 1852.91  5018.6 1853.49  5039.3 1853.87
  5045.1 1853.59  5050.3 1854.86  5060.0 1854.83  5111.7 1856.24  5263.5 1857.48
#Mann=3,-1,0
  4630.0    0.05       0  4983.4    0.05       0  4987.9    0.05       0
Bank Sta=4983.4,4987.9
Exp/Cntr=0.3,0.1

Chan Stop Cuts=-1