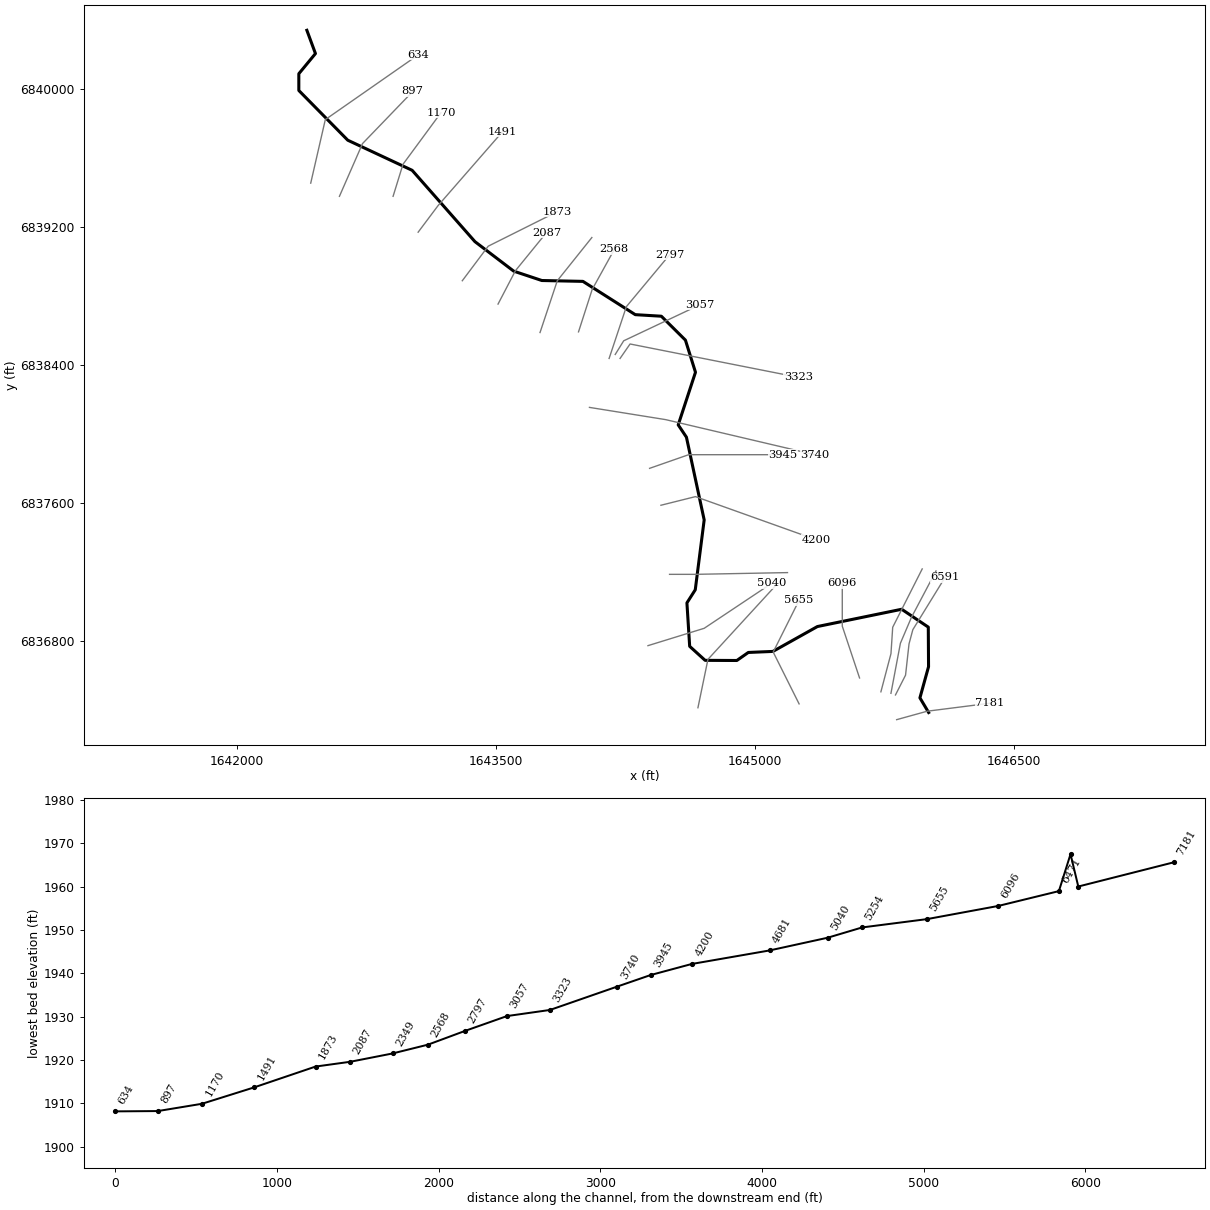
--- Deadman 61.prj (project) ---

Proj Title=Deadman 61 Base Level Engineering
Current Plan=p01
Default Exp/Contr=0.3,0.1
English Units
Geom File=g01
Flow File=f01
Plan File=p01
BEGIN DESCRIPTION:
Deadman 61
END DESCRIPTION:

--- Deadman 61.p01 (plan) ---

Plan Title=Multiple Run
Short Identifier=Multiple
Geom File=g01
Flow File=f01
Subcritical Flow
K Sum by GR= 0
Std Step Tol= 0.01
Critical Tol= 0.01
Num of Std Step Trials= 20
Max Error Tol= 0.3
Flow Tol Ratio= 0.001
Split Flow NTrial= 30
Split Flow Tol= 0.02
Split Flow Ratio= 0.02
Log Output Level= 0
Friction Slope Method= 1
Unsteady Friction Slope Method= 2
Unsteady Bridges Friction Slope Method= 1
Parabolic Critical Depth
Global Vel Dist=  1 , 1 , 1
Global Log Level= 0
CheckData=True
Encroach Param= -1, 0, 0, 0
BEGIN DESCRIPTION:
Multiple Run
END DESCRIPTION:

--- Deadman 61.f01 (steady flow) ---

Flow Title=Multiple
Number of Profiles=7
Profile Names=10-year,25-year,50-year,1pct_min,100-year,1pct_plu,500-year
River Rch & RM= Deadman 61,Reach-1,7181
     181     244     294     176     352     702     511
River Rch & RM= Deadman 61,Reach-1,6591
     281     390     479     294     586    1169     886
Boundary for River Rch & Prof#=Deadman 61,Reach-1,1
Up Type=0
Dn Type=3
Dn Slope=0.005
Boundary for River Rch & Prof#=Deadman 61,Reach-1,2
Up Type=0
Dn Type=3
Dn Slope=0.005
Boundary for River Rch & Prof#=Deadman 61,Reach-1,3
Up Type=0
Dn Type=3
Dn Slope=0.005
Boundary for River Rch & Prof#=Deadman 61,Reach-1,4
Up Type=0
Dn Type=3
Dn Slope=0.005
Boundary for River Rch & Prof#=Deadman 61,Reach-1,5
Up Type=0
Dn Type=3
Dn Slope=0.005
Boundary for River Rch & Prof#=Deadman 61,Reach-1,6
Up Type=0
Dn Type=3
Dn Slope=0.005
Boundary for River Rch & Prof#=Deadman 61,Reach-1,7
Up Type=0
Dn Type=3
Dn Slope=0.005

--- Deadman 61.g01 (geometry) ---

Geom Title=Existing Conditions

River Reach=Deadman 61,Reach-1
Reach XY= 30
      1646005.00      6836388.00      1645954.55      6836472.85
      1646004.48      6836653.22      1646003.02      6836882.33
      1645849.04      6836985.86      1645360.93      6836885.75
      1645103.44      6836741.76      1644960.94      6836735.73
      1644894.49      6836689.22      1644710.84      6836690.05
      1644621.41      6836771.20      1644605.52      6837022.78
      1644653.78      6837098.51      1644705.43      6837503.18
      1644602.70      6837982.07      1644555.09      6838053.39
      1644655.10      6838358.10      1644596.86      6838544.06
      1644457.45      6838682.53      1644306.47      6838691.55
      1644003.45      6838884.25      1643765.50      6838889.22
      1643602.57      6838943.52      1643378.18      6839114.30
      1643014.68      6839527.24      1642641.79      6839701.62
      1642358.46      6839989.50      1642358.47      6840086.50
      1642454.77      6840203.20      1642405.00      6840338.00

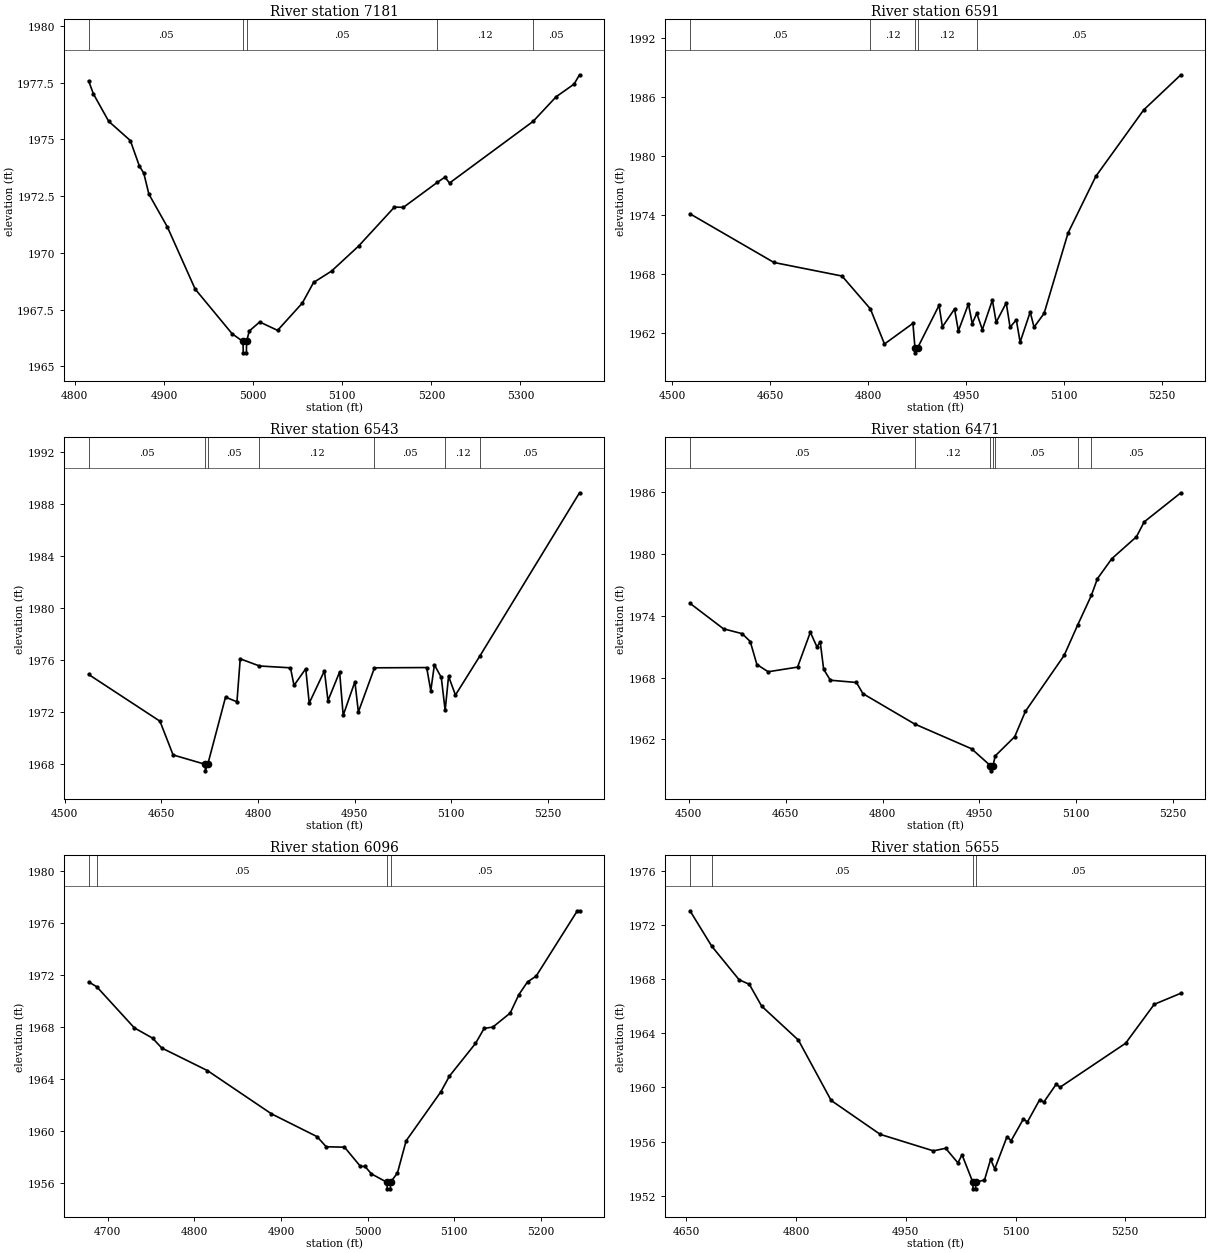
Type RM Length L Ch R = 1,7181,590,590,590
BEGIN DESCRIPTION:
Deadman 61 12.0
END DESCRIPTION:
XS GIS Cut Line= 3
      1645819.85      6836346.59      1645997.00      6836395.65
      1646361.07      6836441.84
#Sta/Elev= 30
  4815.5 1977.58  4820.8 1977.01  4838.0 1975.80  4862.3 1974.95  4872.3 1973.84
  4877.4 1973.51  4883.1 1972.59  4903.9 1971.14  4935.0 1968.41  4976.5 1966.44
  4988.7 1966.10  4989.0 1965.60  4992.5 1965.60  4992.7 1966.10  4995.7 1966.56
  5007.4 1966.96  5027.5 1966.59  5055.2 1967.79  5067.9 1968.70  5088.0 1969.20
  5118.3 1970.30  5158.6 1972.02  5168.7 1972.01  5206.7 1973.11  5215.3 1973.34
  5220.4 1973.08  5314.3 1975.80  5340.0 1976.88  5360.2 1977.44  5366.3 1977.85
#Mann=5,-1,0
  4815.5    0.05       0  4988.7    0.03       0  4992.7    0.05       0
  5206.7    0.12       0  5314.3    0.05       0
Bank Sta=4988.7,4992.7
Exp/Cntr=0.3,0.1

Type RM Length L Ch R = 1,6591,48,48,48
BEGIN DESCRIPTION:
Mapping XS 2b95ed2a
END DESCRIPTION:
XS GIS Cut Line= 5
      1645813.04      6836489.74      1645871.34      6836604.31
      1645891.44      6836785.20      1645913.54      6836867.61
      1646100.25      6837170.75
#Sta/Elev= 30
  4526.9 1974.16  4655.5 1969.21  4759.8 1967.83  4803.2 1964.49  4824.8 1960.92
  4868.4 1963.02  4871.5 1960.52  4871.8 1960.02  4875.5 1960.52  4908.4 1964.85
  4913.5 1962.66  4932.1 1964.48  4938.0 1962.25  4953.4 1964.99  4959.2 1963.00
  4966.2 1964.04  4974.7 1962.38  4990.1 1965.38  4995.9 1963.13  5011.3 1965.10
  5017.2 1962.62  5026.7 1963.38  5032.6 1961.11  5048.0 1964.17  5053.9 1962.63
  5069.3 1964.03  5106.0 1972.21  5148.5 1977.97  5221.9 1984.73  5278.8 1988.30
#Mann=5,-1,0
  4526.9    0.05       0  4803.2    0.12       0  4871.5    0.05       0
  4875.5    0.12       0  4966.2    0.05       0
Bank Sta=4871.5,4875.5
Exp/Cntr=0.3,0.1

Type RM Length L Ch R = 1,6543,72,72,72
BEGIN DESCRIPTION:
Deadman 61 11.0
END DESCRIPTION:
XS GIS Cut Line= 4
      1645786.80      6836499.21      1645841.56      6836789.10
      1645905.00      6836938.00      1646047.66      6837207.74
#Sta/Elev= 30
  4537.2 1974.89  4647.9 1971.30  4668.3 1968.71  4718.1 1967.99  4718.4 1967.49
  4722.1 1967.99  4749.7 1973.15  4767.4 1972.79  4772.5 1976.09  4802.4 1975.54
  4850.5 1975.40  4856.0 1974.05  4874.2 1975.33  4879.6 1972.69  4903.2 1975.17
  4908.7 1972.88  4926.8 1975.08  4932.3 1971.75  4950.5 1974.33  4955.9 1972.01
  4980.9 1975.40  5061.9 1975.42  5068.3 1973.64  5073.9 1975.63  5084.6 1974.66
  5090.6 1972.13  5095.9 1974.75  5106.6 1973.31  5144.3 1976.29  5299.2 1988.84
#Mann=7,-1,0
  4537.2    0.05       0  4718.1    0.05       0  4722.1    0.05       0
  4802.4    0.12       0  4980.9    0.05       0  5090.6    0.12       0
  5144.3    0.05       0
Bank Sta=4718.1,4722.1
Exp/Cntr=0.3,0.1

Type RM Length L Ch R = 1,6471,375,375,375
BEGIN DESCRIPTION:
Mapping XS 04c24675
END DESCRIPTION:
XS GIS Cut Line= 4
      1645728.63      6836507.81      1645786.92      6836728.93
      1645796.97      6836881.68      1645967.82      6837219.36
#Sta/Elev= 30
  4501.8 1975.19  4553.7 1972.72  4582.6 1972.25  4595.1 1971.49  4605.4 1969.26
  4622.9 1968.56  4668.4 1969.01  4688.2 1972.39  4698.3 1970.98  4703.5 1971.44
  4708.8 1968.80  4719.2 1967.74  4759.6 1967.52  4769.6 1966.44  4849.6 1963.50
  4937.8 1961.10  4967.1 1959.46  4967.3 1958.96  4971.1 1959.46  4974.4 1960.40
  5004.7 1962.27  5021.3 1964.73  5081.2 1970.14  5102.2 1973.09  5123.4 1975.96
  5132.8 1977.58  5155.0 1979.51  5193.2 1981.64  5205.2 1983.08  5262.0 1985.90
#Mann=7,-1,0
  4501.8    0.05       0  4849.6    0.12       0  4967.1    0.05       0
  4971.1    0.12       0  4974.4    0.05       0  5102.2    0.12       0
  5123.4    0.05       0
Bank Sta=4967.1,4971.1
Exp/Cntr=0.3,0.1

Type RM Length L Ch R = 1,6096,441,441,441
BEGIN DESCRIPTION:
Deadman 61 10.0
END DESCRIPTION:
XS GIS Cut Line= 3
      1645604.99      6836588.04      1645505.00      6836888.00
      1645505.00      6837138.02
#Sta/Elev= 30
  4678.2 1971.48  4687.5 1971.11  4730.9 1967.94  4751.9 1967.15  4762.5 1966.39
  4815.2 1964.65  4889.0 1961.32  4941.7 1959.56  4952.2 1958.78  4973.3 1958.75
  4991.7 1957.27  4996.9 1957.27  5004.4 1956.69  5022.4 1956.04  5022.6 1955.54
  5026.1 1955.54  5026.4 1956.04  5034.4 1956.77  5044.4 1959.24  5084.4 1963.01
  5094.4 1964.23  5124.4 1966.74  5134.4 1967.90  5144.4 1968.00  5164.4 1969.08
  5174.4 1970.50  5184.4 1971.48  5194.4 1971.93  5241.9 1976.96  5244.4 1976.96
#Mann=4,-1,0
  4678.2    0.12       0  4687.5    0.05       0  5022.4    0.05       0
  5026.4    0.05       0
Bank Sta=5022.4,5026.4
Exp/Cntr=0.3,0.1

Type RM Length L Ch R = 1,5655,401,401,401
BEGIN DESCRIPTION:
Deadman 61 9.0
END DESCRIPTION:
XS GIS Cut Line= 3
      1645255.01      6836437.97      1645105.00      6836738.00
      1645255.02      6837038.04
#Sta/Elev= 30
  4655.1 1973.07  4684.7 1970.46  4722.2 1967.97  4736.2 1967.63  4753.0 1966.02
  4803.3 1963.50  4848.0 1959.04  4915.1 1956.53  4987.7 1955.31  5004.5 1955.50
  5021.3 1954.42  5026.9 1955.02  5041.6 1953.00  5041.9 1952.50  5045.4 1952.50
  5045.6 1953.00  5057.6 1953.15  5066.0 1954.68  5071.6 1953.97  5088.4 1956.36
  5094.0 1956.06  5110.7 1957.66  5116.3 1957.45  5133.1 1959.10  5138.7 1958.92
  5155.5 1960.23  5161.0 1960.02  5250.5 1963.27  5289.6 1966.15  5326.0 1966.97
#Mann=4,-1,0
  4655.1    0.12       0  4684.7    0.05       0  5041.6    0.05       0
  5045.6    0.05       0
Bank Sta=5041.6,5045.6
Exp/Cntr=0.3,0.1

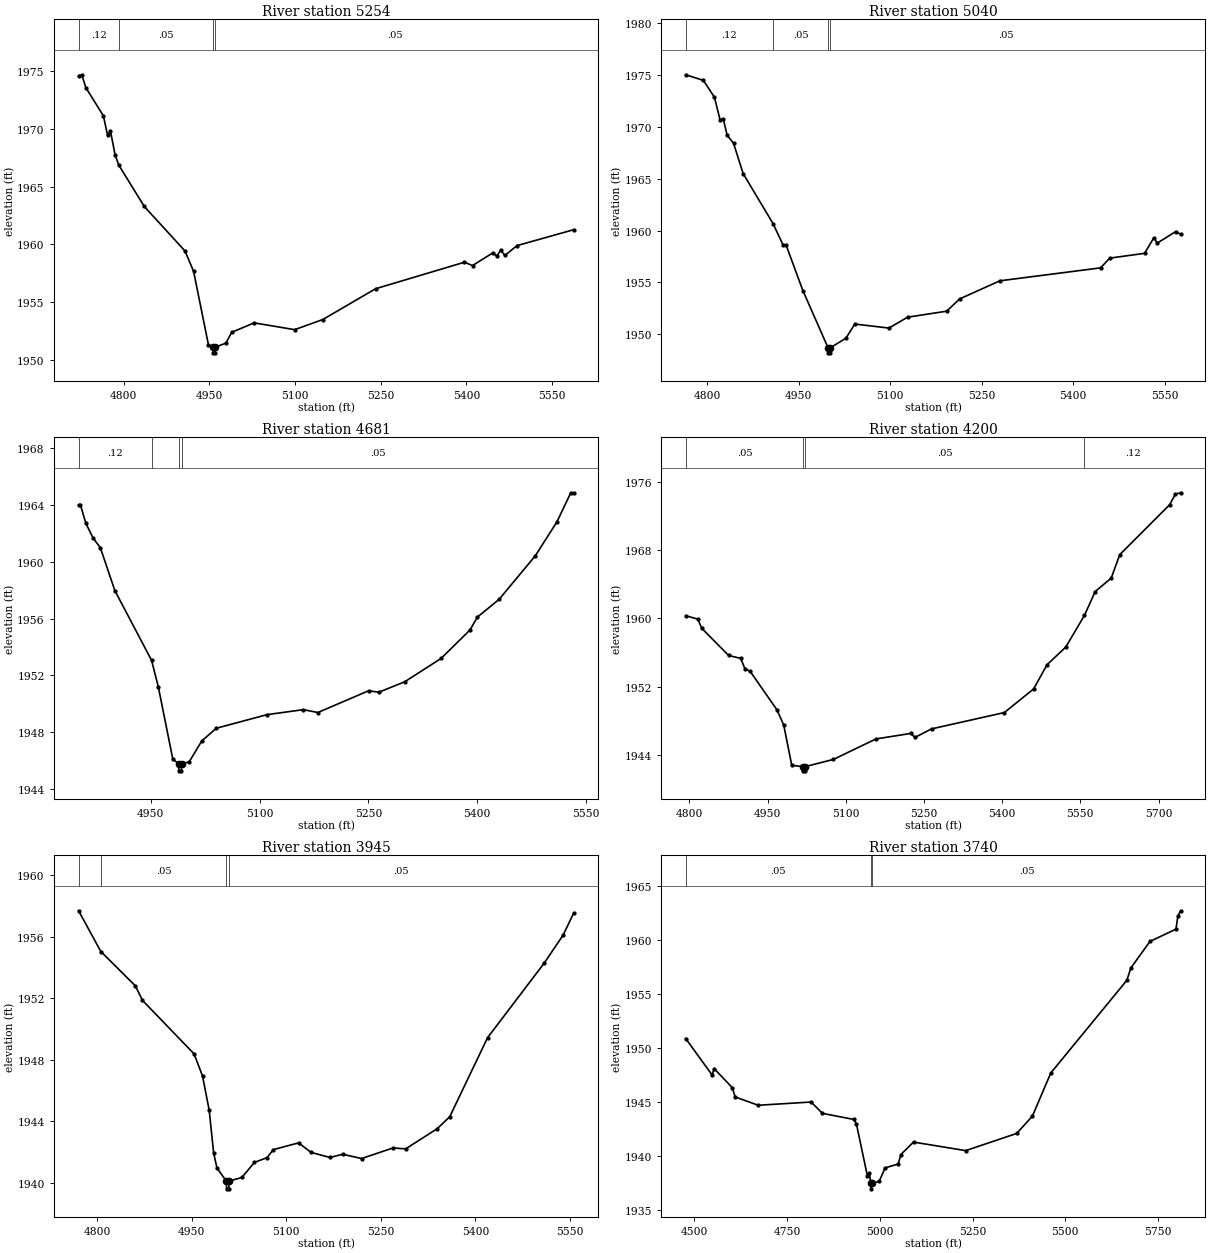
Type RM Length L Ch R = 1,5254,214,214,214
BEGIN DESCRIPTION:
Mapping XS 38c4d867
END DESCRIPTION:
XS GIS Cut Line= 3
      1644669.28      6836415.52      1644727.25      6836695.71
      1645119.57      6837123.40
#Sta/Elev= 30
  4721.0 1974.62  4726.6 1974.70  4733.7 1973.58  4764.4 1971.14  4771.7 1969.45
  4776.8 1969.81  4784.8 1967.77  4791.3 1966.87  4835.9 1963.28  4907.3 1959.41
  4922.3 1957.65  4948.2 1951.30  4956.4 1951.08  4956.7 1950.58  4960.2 1950.58
  4960.4 1951.08  4978.8 1951.42  4989.0 1952.36  5028.3 1953.18  5099.2 1952.59
  5148.5 1953.47  5240.9 1956.14  5396.4 1958.44  5410.6 1958.15  5445.7 1959.24
  5453.1 1958.99  5459.9 1959.47  5467.3 1959.03  5488.3 1959.88  5587.5 1961.26
#Mann=4,-1,0
  4721.0    0.12       0  4791.3    0.05       0  4956.4    0.05       0
  4960.4    0.05       0
Bank Sta=4956.4,4960.4
Exp/Cntr=0.3,0.1

Type RM Length L Ch R = 1,5040,359,359,359
BEGIN DESCRIPTION:
Mapping XS 3bebd150
END DESCRIPTION:
XS GIS Cut Line= 3
      1644380.03      6836775.16      1644705.61      6836875.65
      1645097.56      6837136.94
#Sta/Elev= 30
  4764.5 1975.03  4793.5 1974.49  4811.6 1972.87  4820.9 1970.69  4826.1 1970.77
  4832.5 1969.20  4843.0 1968.42  4858.8 1965.49  4907.8 1960.67  4924.1 1958.62
  4929.3 1958.58  4956.7 1954.21  4997.9 1948.70  4998.1 1948.20  5001.7 1948.20
  5002.0 1948.70  5027.3 1949.61  5041.8 1950.98  5097.8 1950.59  5128.5 1951.64
  5192.6 1952.22  5213.7 1953.40  5279.8 1955.15  5445.0 1956.40  5460.0 1957.34
  5517.1 1957.80  5532.1 1959.28  5538.2 1958.80  5568.2 1959.90  5576.3 1959.63
#Mann=4,-1,0
  4764.5    0.12       0  4907.8    0.05       0  4997.9    0.05       0
  5002.0    0.05       0
Bank Sta=4997.9,5002
Exp/Cntr=0.3,0.1

Type RM Length L Ch R = 1,4681,481,481,481
BEGIN DESCRIPTION:
Deadman 61 8.0
END DESCRIPTION:
XS GIS Cut Line= 3
      1644504.98      6837188.00      1644655.00      6837188.00
      1645187.78      6837198.11
#Sta/Elev= 30
  4850.3 1964.01  4852.8 1964.01  4860.3 1962.71  4870.3 1961.67  4880.3 1960.99
  4900.3 1957.97  4951.0 1953.05  4960.3 1951.18  4980.3 1946.09  4988.3 1945.77
  4988.5 1945.27  4992.1 1945.27  4992.4 1945.77  5002.8 1945.90  5020.3 1947.38
  5040.3 1948.27  5110.3 1949.23  5160.4 1949.58  5180.4 1949.38  5250.4 1950.91
  5264.6 1950.81  5300.4 1951.55  5350.4 1953.19  5390.4 1955.20  5400.4 1956.10
  5430.4 1957.35  5480.4 1960.42  5510.4 1962.83  5529.3 1964.86  5533.2 1964.86
#Mann=4,-1,0
  4850.3    0.12       0  4951.0    0.05       0  4988.3    0.03       0
  4992.4    0.05       0
Bank Sta=4988.3,4992.4
Exp/Cntr=0.3,0.1

Type RM Length L Ch R = 1,4200,255,255,255
BEGIN DESCRIPTION:
Deadman 61 7.0
END DESCRIPTION:
XS GIS Cut Line= 3
      1644455.03      6837588.01      1644655.00      6837638.00
      1645354.98      6837388.01
#Sta/Elev= 30
  4793.0 1960.30  4816.2 1959.91  4823.9 1958.83  4875.4 1955.65  4898.6 1955.31
  4906.4 1954.12  4916.7 1953.79  4968.2 1949.28  4981.1 1947.50  4996.5 1942.79
  5018.3 1942.65  5018.6 1942.15  5022.2 1942.15  5022.5 1942.65  5076.1 1943.48
  5157.9 1945.88  5224.8 1946.53  5232.7 1946.06  5264.6 1947.06  5404.2 1948.97
  5460.5 1951.74  5486.0 1954.56  5522.1 1956.64  5557.9 1960.35  5578.4 1963.13
  5609.2 1964.71  5625.6 1967.45  5721.2 1973.29  5732.3 1974.53  5742.4 1974.69
#Mann=4,-1,0
  4793.0    0.05       0  5018.3    0.05       0  5022.5    0.05       0
  5557.9    0.12       0
Bank Sta=5018.3,5022.5
Exp/Cntr=0.3,0.1

Type RM Length L Ch R = 1,3945,205,205,205
BEGIN DESCRIPTION:
Mapping XS cc092711
END DESCRIPTION:
XS GIS Cut Line= 3
      1644389.32      6837801.71      1644615.47      6837880.73
      1645161.61      6837880.73
#Sta/Elev= 30
  4770.3 1957.68  4805.6 1955.03  4860.5 1952.79  4871.7 1951.85  4953.6 1948.37
  4967.0 1946.93  4977.6 1944.70  4984.7 1941.90  4990.0 1940.94  5004.9 1940.09
  5005.2 1939.59  5008.8 1939.59  5009.1 1940.09  5029.4 1940.33  5049.4 1941.31
  5069.4 1941.62  5079.4 1942.14  5119.4 1942.58  5139.4 1941.96  5169.4 1941.63
  5189.4 1941.84  5219.4 1941.56  5269.4 1942.25  5289.4 1942.19  5339.4 1943.50
  5359.4 1944.28  5419.4 1949.42  5509.4 1954.28  5539.4 1956.10  5556.0 1957.52
#Mann=4,-1,0
  4770.3    0.12       0  4805.6    0.05       0  5004.9    0.05       0
  5009.1    0.05       0
Bank Sta=5004.9,5009.1
Exp/Cntr=0.3,0.1

Type RM Length L Ch R = 1,3740,417,417,417
BEGIN DESCRIPTION:
Mapping XS 75ac1db9
END DESCRIPTION:
XS GIS Cut Line= 3
      1644041.26      6838154.62      1644482.49      6838083.76
      1645345.58      6837880.87
#Sta/Elev= 30
  4477.2 1950.87  4548.7 1947.48  4553.7 1948.09  4602.5 1946.33  4610.6 1945.46
  4672.5 1944.69  4815.2 1944.99  4845.6 1943.94  4929.6 1943.38  4936.9 1943.00
  4966.9 1938.12  4972.0 1938.44  4975.9 1937.45  4976.2 1936.95  4980.1 1937.45
  4998.6 1937.65  5014.4 1938.89  5049.9 1939.25  5056.8 1940.12  5091.0 1941.28
  5231.5 1940.49  5369.0 1942.08  5411.4 1943.69  5460.8 1947.68  5665.7 1956.26
  5676.6 1957.41  5727.9 1959.86  5798.1 1961.00  5803.2 1962.23  5810.7 1962.70
#Mann=3,-1,0
  4477.2    0.05       0  4975.9    0.05       0  4980.1    0.05       0
Bank Sta=4975.9,4980.1
Exp/Cntr=0.3,0.1

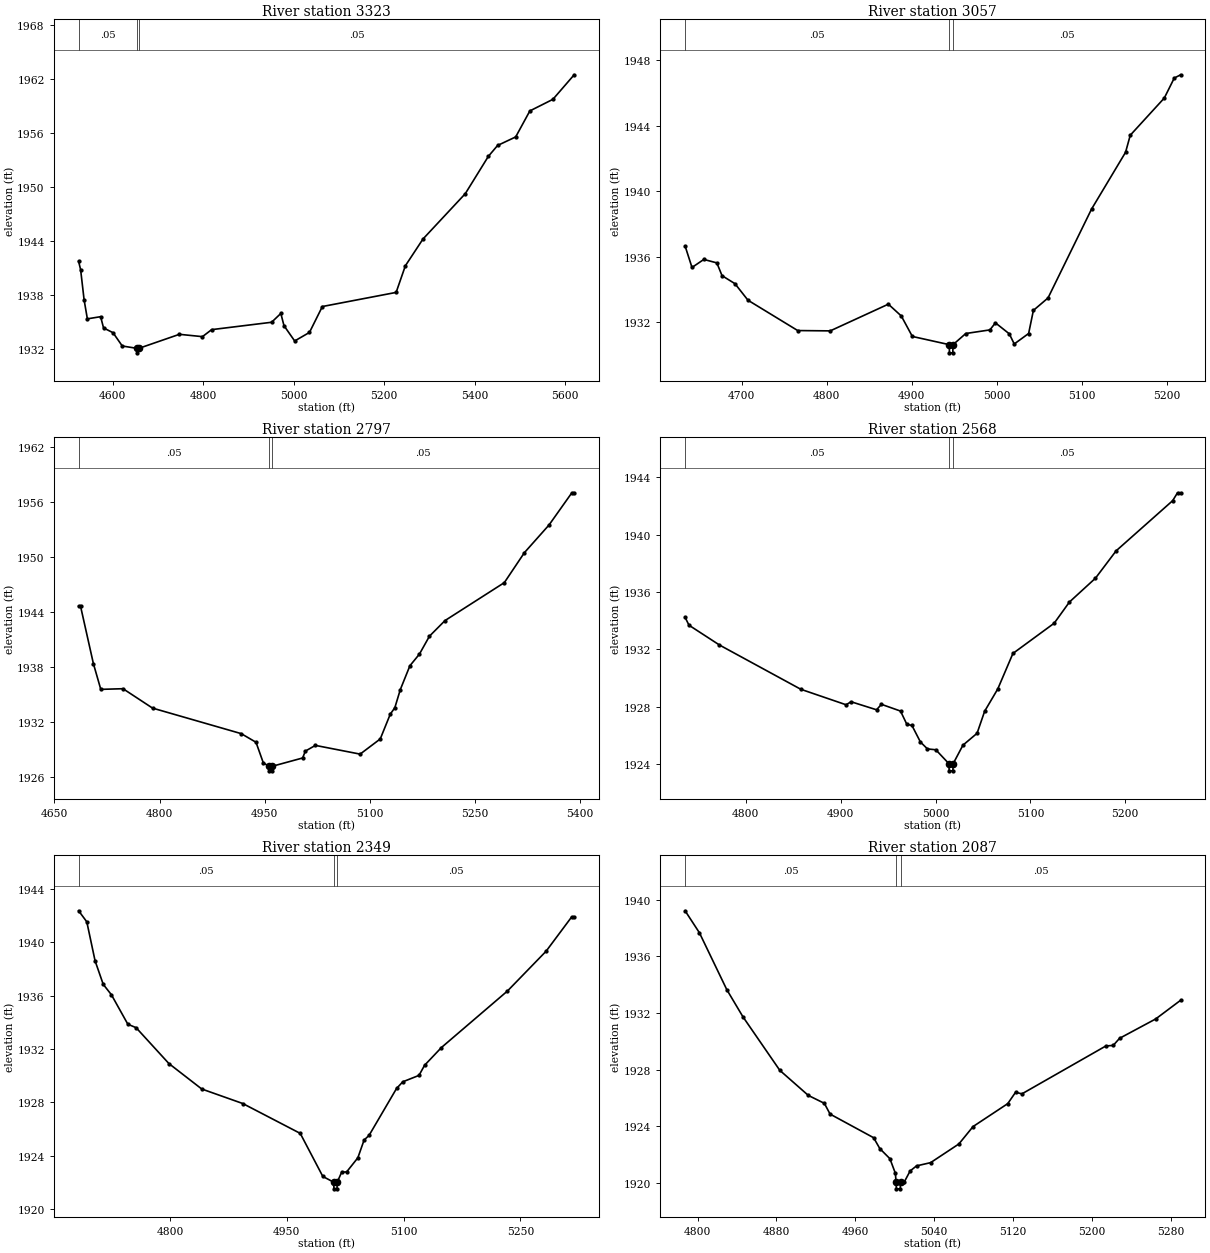
Type RM Length L Ch R = 1,3323,266,266,266
BEGIN DESCRIPTION:
Mapping XS 283b312f
END DESCRIPTION:
XS GIS Cut Line= 3
      1644218.41      6838438.04      1644276.37      6838521.76
      1645251.12      6838328.74
#Sta/Elev= 30
  4524.5 1941.70  4528.9 1940.79  4536.6 1937.43  4543.8 1935.32  4573.1 1935.56
  4579.6 1934.31  4600.5 1933.78  4621.0 1932.30  4653.4 1932.04  4653.7 1931.54
  4657.7 1932.04  4747.3 1933.60  4798.2 1933.34  4818.6 1934.12  4951.1 1934.94
  4971.5 1935.92  4978.5 1934.56  5002.1 1932.86  5034.8 1933.81  5063.3 1936.69
  5226.4 1938.26  5246.8 1941.22  5285.8 1944.20  5379.3 1949.24  5430.3 1953.39
  5450.7 1954.60  5490.7 1955.55  5522.0 1958.44  5573.0 1959.73  5620.0 1962.46
#Mann=3,-1,0
  4524.5    0.05       0  4653.4    0.03       0  4657.7    0.05       0
Bank Sta=4653.4,4657.7
Exp/Cntr=0.3,0.1

Type RM Length L Ch R = 1,3057,260,260,260
BEGIN DESCRIPTION:
Mapping XS 814dc509
END DESCRIPTION:
XS GIS Cut Line= 3
      1644190.40      6838461.15      1644239.43      6838540.15
      1644681.78      6838749.12
#Sta/Elev= 30
  4633.6 1936.65  4641.7 1935.34  4655.6 1935.83  4670.9 1935.62  4677.0 1934.84
  4692.2 1934.35  4707.5 1933.34  4765.9 1931.49  4804.1 1931.47  4872.4 1933.10
  4887.6 1932.38  4900.6 1931.13  4943.9 1930.63  4944.2 1930.13  4948.1 1930.13
  4948.4 1930.63  4963.4 1931.31  4991.7 1931.53  4998.2 1931.96  5014.5 1931.29
  5020.3 1930.67  5037.2 1931.31  5042.8 1932.72  5060.0 1933.48  5111.1 1938.90
  5151.1 1942.37  5156.6 1943.41  5196.6 1945.68  5208.3 1946.90  5215.8 1947.10
#Mann=3,-1,0
  4633.6    0.05       0  4943.9    0.05       0  4948.4    0.05       0
Bank Sta=4943.9,4948.4
Exp/Cntr=0.3,0.1

Type RM Length L Ch R = 1,2797,229,229,229
BEGIN DESCRIPTION:
Deadman 61 4.0
END DESCRIPTION:
XS GIS Cut Line= 3
      1644154.99      6838437.98      1644255.00      6838738.00
      1644505.02      6839038.03
#Sta/Elev= 30
  4684.6 1944.63  4687.3 1944.63  4705.7 1938.36  4716.2 1935.57  4747.9 1935.64
  4790.0 1933.53  4916.5 1930.75  4937.6 1929.81  4948.1 1927.55  4956.4 1927.20
  4956.7 1926.70  4960.6 1926.70  4960.9 1927.20  5004.1 1928.10  5008.0 1928.85
  5022.3 1929.47  5086.1 1928.52  5114.8 1930.17  5129.1 1932.87  5135.6 1933.57
  5143.4 1935.54  5157.1 1938.14  5170.7 1939.41  5185.0 1941.36  5207.2 1943.06
  5291.8 1947.19  5320.4 1950.45  5355.6 1953.47  5388.1 1956.97  5391.4 1956.97
#Mann=3,-1,0
  4684.6    0.05       0  4956.4    0.05       0  4960.9    0.05       0
Bank Sta=4956.4,4960.9
Exp/Cntr=0.3,0.1

Type RM Length L Ch R = 1,2568,219,219,219
BEGIN DESCRIPTION:
Mapping XS 1fcff857
END DESCRIPTION:
XS GIS Cut Line= 3
      1643977.83      6838591.88      1644056.86      6838837.17
      1644184.95      6839068.81
#Sta/Elev= 30
  4736.0 1934.24  4740.1 1933.69  4772.2 1932.31  4858.0 1929.22  4905.7 1928.14
  4911.0 1928.35  4937.8 1927.79  4943.0 1928.17  4963.1 1927.70  4969.8 1926.77
  4975.1 1926.70  4984.1 1925.54  4991.5 1925.06  5000.3 1925.00  5014.1 1924.03
  5014.4 1923.53  5018.3 1923.53  5018.6 1924.03  5028.9 1925.32  5043.8 1926.15
  5051.8 1927.69  5065.6 1929.24  5081.6 1931.72  5125.1 1933.83  5141.2 1935.31
  5168.6 1936.97  5190.4 1938.88  5250.0 1942.38  5255.1 1942.93  5258.4 1942.93
#Mann=3,-1,0
  4736.0    0.05       0  5014.1    0.05       0  5018.6    0.05       0
Bank Sta=5014.1,5018.6
Exp/Cntr=0.3,0.1

Type RM Length L Ch R = 1,2349,262,262,262
BEGIN DESCRIPTION:
Deadman 61 3.0
END DESCRIPTION:
XS GIS Cut Line= 3
      1643755.01      6838588.02      1643855.00      6838888.00
      1644055.02      6839138.03
#Sta/Elev= 30
  4682.7 1942.36  4693.2 1941.53  4703.8 1938.61  4714.3 1936.84  4724.8 1936.06
  4745.9 1933.85  4756.5 1933.59  4798.6 1930.90  4840.8 1928.99  4893.5 1927.90
  4967.3 1925.66  4996.3 1922.43  5010.2 1922.00  5010.6 1921.50  5014.5 1921.50
  5014.8 1922.00  5020.5 1922.75  5026.9 1922.77  5041.3 1923.83  5049.3 1925.16
  5055.7 1925.51  5091.0 1929.03  5099.0 1929.53  5119.8 1930.01  5127.0 1930.77
  5148.6 1932.10  5233.4 1936.34  5283.1 1939.33  5315.9 1941.90  5319.1 1941.90
#Mann=3,-1,0
  4682.7    0.05       0  5010.2    0.05       0  5014.8    0.05       0
Bank Sta=5010.2,5014.8
Exp/Cntr=0.3,0.1

Type RM Length L Ch R = 1,2087,214,214,214
BEGIN DESCRIPTION:
Mapping XS 4c0dc6e8
END DESCRIPTION:
XS GIS Cut Line= 3
      1643511.90      6838752.74      1643612.70      6838946.17
      1643792.53      6839166.86
#Sta/Elev= 30
  4787.3 1939.22  4801.8 1937.67  4829.6 1933.65  4846.0 1931.73  4883.4 1927.95
  4912.3 1926.18  4928.6 1925.62  4934.4 1924.86  4978.6 1923.19  4984.9 1922.42
  4995.1 1921.71  5000.7 1920.67  5001.3 1920.08  5001.7 1919.58  5005.6 1919.58
  5005.9 1920.08  5009.8 1920.08  5015.6 1920.84  5022.1 1921.20  5036.4 1921.43
  5065.1 1922.75  5079.5 1923.98  5114.7 1925.60  5122.6 1926.40  5129.1 1926.29
  5214.2 1929.67  5221.7 1929.71  5228.1 1930.21  5264.8 1931.58  5290.1 1932.90
#Mann=3,-1,0
  4787.3    0.05       0  5001.3    0.05       0  5005.9    0.05       0
Bank Sta=5001.3,5005.9
Exp/Cntr=0.3,0.1

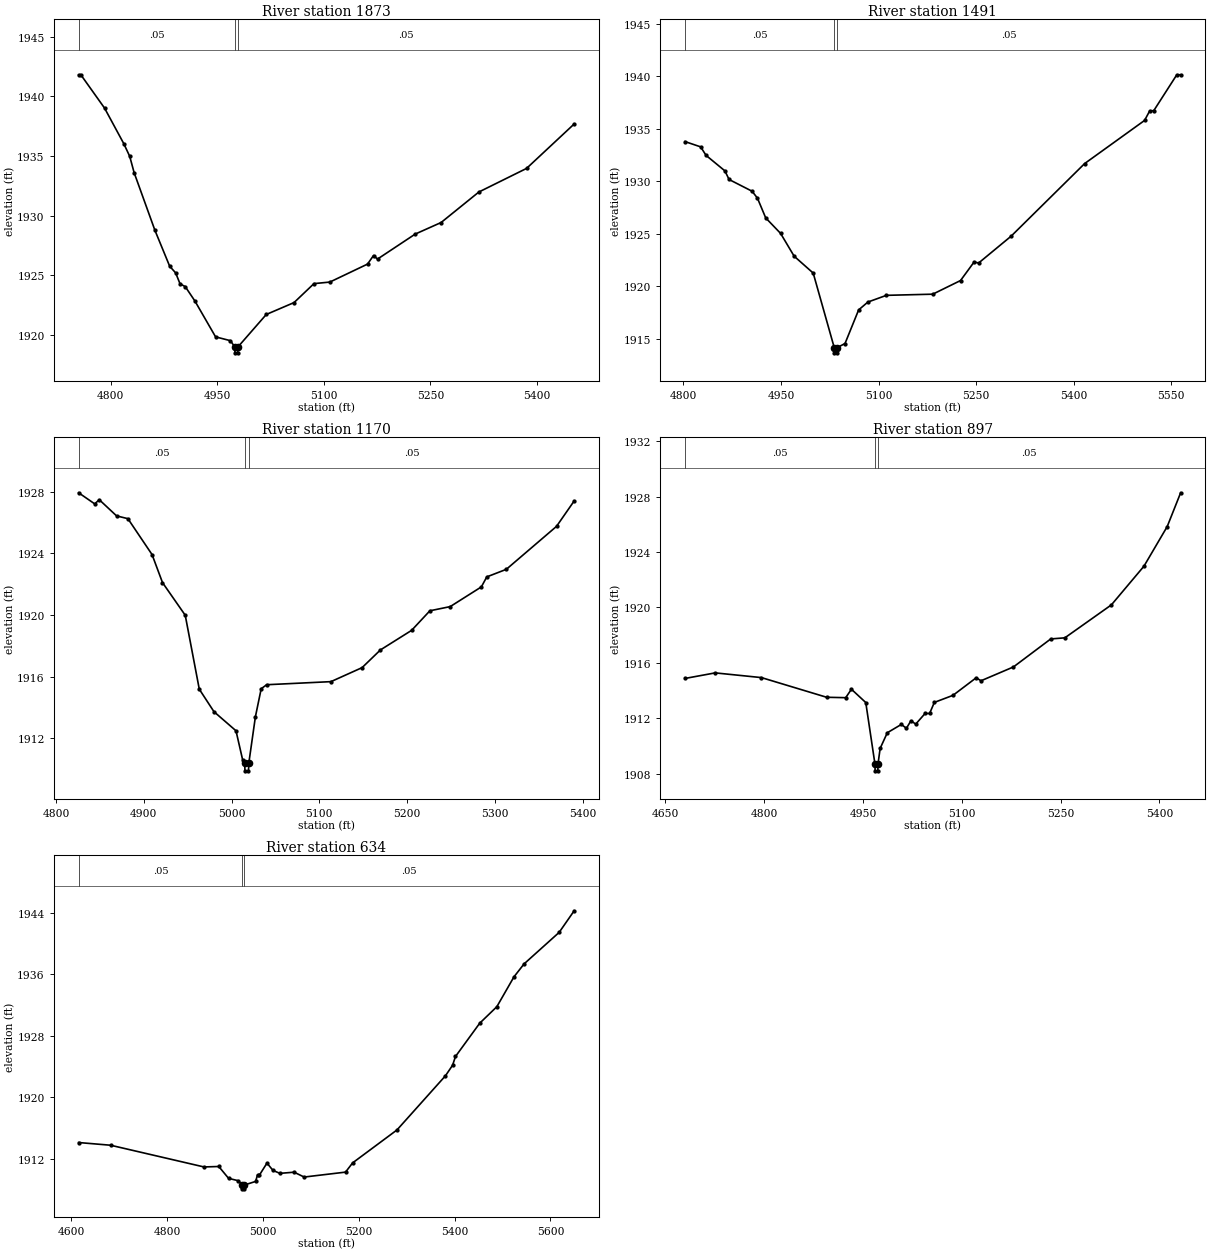
Type RM Length L Ch R = 1,1873,382,382,382
BEGIN DESCRIPTION:
Deadman 61 2.0
END DESCRIPTION:
XS GIS Cut Line= 3
      1643304.99      6838887.98      1643455.00      6839088.00
      1643854.97      6839287.98
#Sta/Elev= 30
  4755.1 1941.82  4758.2 1941.82  4791.6 1939.02  4818.7 1936.03  4827.0 1934.97
  4833.2 1933.60  4862.4 1928.77  4883.2 1925.75  4891.6 1925.19  4897.8 1924.27
  4905.1 1924.04  4918.7 1922.83  4947.8 1919.82  4968.7 1919.50  4974.7 1918.98
  4975.0 1918.48  4978.9 1918.48  4979.3 1918.98  5019.1 1921.70  5058.2 1922.70
  5086.2 1924.29  5108.5 1924.42  5161.6 1925.93  5170.0 1926.65  5175.6 1926.35
  5228.7 1928.45  5265.1 1929.42  5318.2 1931.98  5385.3 1933.96  5452.3 1937.69
#Mann=3,-1,0
  4755.1    0.05       0  4974.7    0.05       0  4979.3    0.05       0
Bank Sta=4974.7,4979.3
Exp/Cntr=0.3,0.1

Type RM Length L Ch R = 1,1491,321,321,321
BEGIN DESCRIPTION:
Mapping XS ed21d41a
END DESCRIPTION:
XS GIS Cut Line= 3
      1643049.32      6839169.05      1643165.28      6839323.68
      1643538.84      6839751.98
#Sta/Elev= 30
  4802.7 1933.78  4826.6 1933.28  4834.9 1932.47  4863.9 1930.99  4870.3 1930.17
  4905.7 1929.05  4913.9 1928.39  4926.6 1926.51  4949.5 1925.03  4970.3 1922.86
  4999.6 1921.25  5031.9 1914.15  5032.2 1913.65  5036.2 1913.65  5036.5 1914.15
  5048.5 1914.54  5069.4 1917.74  5083.6 1918.49  5112.1 1919.13  5183.3 1919.24
  5226.0 1920.54  5246.9 1922.31  5253.8 1922.21  5303.8 1924.77  5416.8 1931.69
  5508.9 1935.80  5516.5 1936.68  5523.1 1936.74  5558.4 1940.15  5564.3 1940.15
#Mann=3,-1,0
  4802.7    0.05       0  5031.9    0.03       0  5036.5    0.05       0
Bank Sta=5031.9,5036.5
Exp/Cntr=0.3,0.1

Type RM Length L Ch R = 1,1170,273,273,273
BEGIN DESCRIPTION:
Mapping XS 0dd07e0a
END DESCRIPTION:
XS GIS Cut Line= 3
      1642904.24      6839376.74      1642961.45      6839562.00
      1643181.09      6839860.27
#Sta/Elev= 30
  4825.9 1927.94  4844.2 1927.22  4849.4 1927.49  4869.1 1926.44  4882.0 1926.26
  4909.5 1923.93  4921.4 1922.11  4947.3 1919.99  4963.3 1915.19  4980.0 1913.73
  5005.1 1912.49  5012.6 1910.62  5015.0 1910.39  5015.3 1909.89  5019.3 1909.89
  5019.7 1910.39  5027.2 1913.40  5033.8 1915.22  5040.0 1915.48  5113.2 1915.68
  5148.7 1916.59  5169.6 1917.74  5205.1 1919.01  5225.9 1920.28  5249.0 1920.55
  5284.5 1921.83  5290.7 1922.48  5312.9 1922.97  5370.1 1925.76  5390.2 1927.41
#Mann=3,-1,0
  4825.9    0.05       0  5015.0    0.03       0  5019.7    0.05       0
Bank Sta=5015,5019.7
Exp/Cntr=0.3,0.1

Type RM Length L Ch R = 1,897,263,263,263
BEGIN DESCRIPTION:
Mapping XS cc0aba42
END DESCRIPTION:
XS GIS Cut Line= 3
      1642593.59      6839376.71      1642727.11      6839681.89
      1643018.03      6839983.69
#Sta/Elev= 30
  4679.8 1914.88  4725.5 1915.28  4795.7 1914.94  4894.7 1913.52  4923.6 1913.49
  4932.3 1914.10  4954.1 1913.14  4968.0 1908.71  4968.3 1908.21  4972.4 1908.21
  4972.7 1908.71  4975.9 1909.83  4986.8 1910.96  5008.1 1911.56  5015.8 1911.28
  5022.7 1911.83  5029.9 1911.58  5044.1 1912.35  5051.0 1912.35  5058.2 1913.15
  5086.5 1913.66  5121.8 1914.93  5129.0 1914.71  5178.3 1915.71  5234.9 1917.73
  5256.3 1917.81  5327.0 1920.19  5376.4 1922.98  5411.7 1925.84  5432.1 1928.28
#Mann=3,-1,0
  4679.8    0.05       0  4968.0    0.03       0  4972.7    0.05       0
Bank Sta=4968,4972.7
Exp/Cntr=0.3,0.1

Type RM Length L Ch R = 1,634,0,0,0
BEGIN DESCRIPTION:
Deadman 61 1.0
END DESCRIPTION:
XS GIS Cut Line= 3
      1642427.36      6839452.96      1642511.84      6839820.86
      1643050.69      6840196.43
#Sta/Elev= 30
  4615.2 1914.15  4681.9 1913.80  4876.9 1910.98  4907.7 1911.04  4928.2 1909.50
  4948.7 1909.19  4956.6 1908.64  4956.9 1908.14  4961.0 1908.14  4961.3 1908.64
  4984.5 1909.10  4988.6 1909.94  4992.7 1909.94  5008.3 1911.48  5020.9 1910.53
  5035.3 1910.15  5065.0 1910.30  5085.9 1909.67  5172.3 1910.31  5187.1 1911.51
  5279.6 1915.78  5380.8 1922.81  5395.7 1924.18  5401.8 1925.32  5452.4 1929.64
  5488.1 1931.78  5523.9 1935.66  5545.0 1937.34  5618.2 1941.43  5649.5 1944.23
#Mann=3,-1,0
  4615.2    0.05       0  4956.6    0.03       0  4961.3    0.05       0
Bank Sta=4956.6,4961.3
Exp/Cntr=0.3,0.1

Chan Stop Cuts=-1