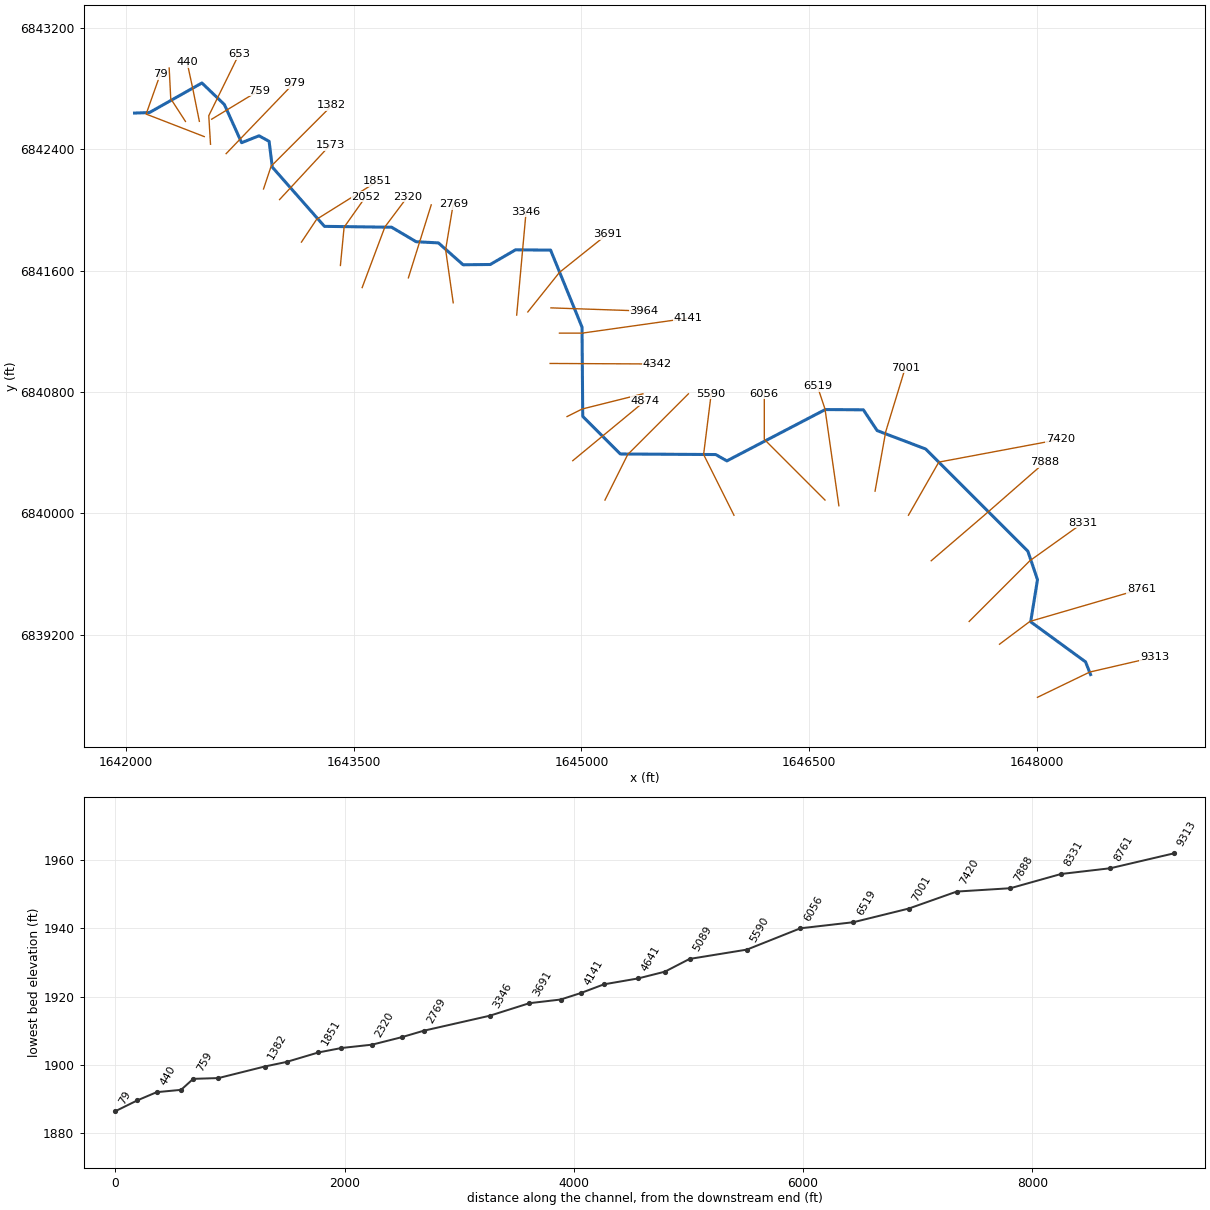
--- Deadman 62.prj (project) ---

Proj Title=Deadman 62 Base Level Engineering
Current Plan=p01
Default Exp/Contr=0.3,0.1
English Units
Geom File=g01
Flow File=f01
Plan File=p01
BEGIN DESCRIPTION:
Deadman 62
END DESCRIPTION:

--- Deadman 62.p01 (plan) ---

Plan Title=Multiple Run
Short Identifier=Multiple
Geom File=g01
Flow File=f01
Subcritical Flow
K Sum by GR= 0
Std Step Tol= 0.01
Critical Tol= 0.01
Num of Std Step Trials= 20
Max Error Tol= 0.3
Flow Tol Ratio= 0.001
Split Flow NTrial= 30
Split Flow Tol= 0.02
Split Flow Ratio= 0.02
Log Output Level= 0
Friction Slope Method= 1
Unsteady Friction Slope Method= 2
Unsteady Bridges Friction Slope Method= 1
Parabolic Critical Depth
Global Vel Dist=  1 , 1 , 1
Global Log Level= 0
CheckData=True
Encroach Param= -1, 0, 0, 0
BEGIN DESCRIPTION:
Multiple Run
END DESCRIPTION:

--- Deadman 62.f01 (steady flow) ---

Flow Title=Multiple
Number of Profiles=7
Profile Names=10-year,25-year,50-year,1pct_min,100-year,1pct_plu,500-year
River Rch & RM= Deadman 62,Reach-1,9313
     189     255     308     186     371     740     542
River Rch & RM= Deadman 62,Reach-1,8761
     345     483     599     370     738    1472    1133
River Rch & RM= Deadman 62,Reach-1,2769
     369     519     646     399     797    1590    1230
Boundary for River Rch & Prof#=Deadman 62,Reach-1,1
Up Type=0
Dn Type=3
Dn Slope=0.009
Boundary for River Rch & Prof#=Deadman 62,Reach-1,2
Up Type=0
Dn Type=3
Dn Slope=0.009
Boundary for River Rch & Prof#=Deadman 62,Reach-1,3
Up Type=0
Dn Type=3
Dn Slope=0.009
Boundary for River Rch & Prof#=Deadman 62,Reach-1,4
Up Type=0
Dn Type=3
Dn Slope=0.009
Boundary for River Rch & Prof#=Deadman 62,Reach-1,5
Up Type=0
Dn Type=3
Dn Slope=0.009
Boundary for River Rch & Prof#=Deadman 62,Reach-1,6
Up Type=0
Dn Type=3
Dn Slope=0.009
Boundary for River Rch & Prof#=Deadman 62,Reach-1,7
Up Type=0
Dn Type=3
Dn Slope=0.009

--- Deadman 62.g01 (geometry) ---

Geom Title=Existing Conditions

River Reach=Deadman 62,Reach-1
Reach XY= 30
      1648355.00      6838938.00      1648322.03      6839021.62
      1647960.39      6839285.56      1648005.23      6839563.07
      1647941.60      6839751.30      1647268.21      6840424.38
      1646948.55      6840545.75      1646857.70      6840682.64
      1646606.55      6840684.25      1645958.30      6840346.08
      1645885.02      6840387.82      1645256.46      6840391.54
      1645008.54      6840639.46      1645003.78      6841227.50
      1644796.72      6841734.94      1644565.50      6841736.80
      1644399.07      6841640.24      1644220.16      6841638.38
      1644057.45      6841782.53      1643910.93      6841790.25
      1643749.07      6841885.76      1643306.46      6841891.54
      1642962.82      6842281.81      1642941.77      6842451.81
      1642875.27      6842488.37      1642760.61      6842442.78
      1642647.14      6842694.17      1642498.95      6842836.42
      1642153.50      6842641.63      1642055.00      6842638.00

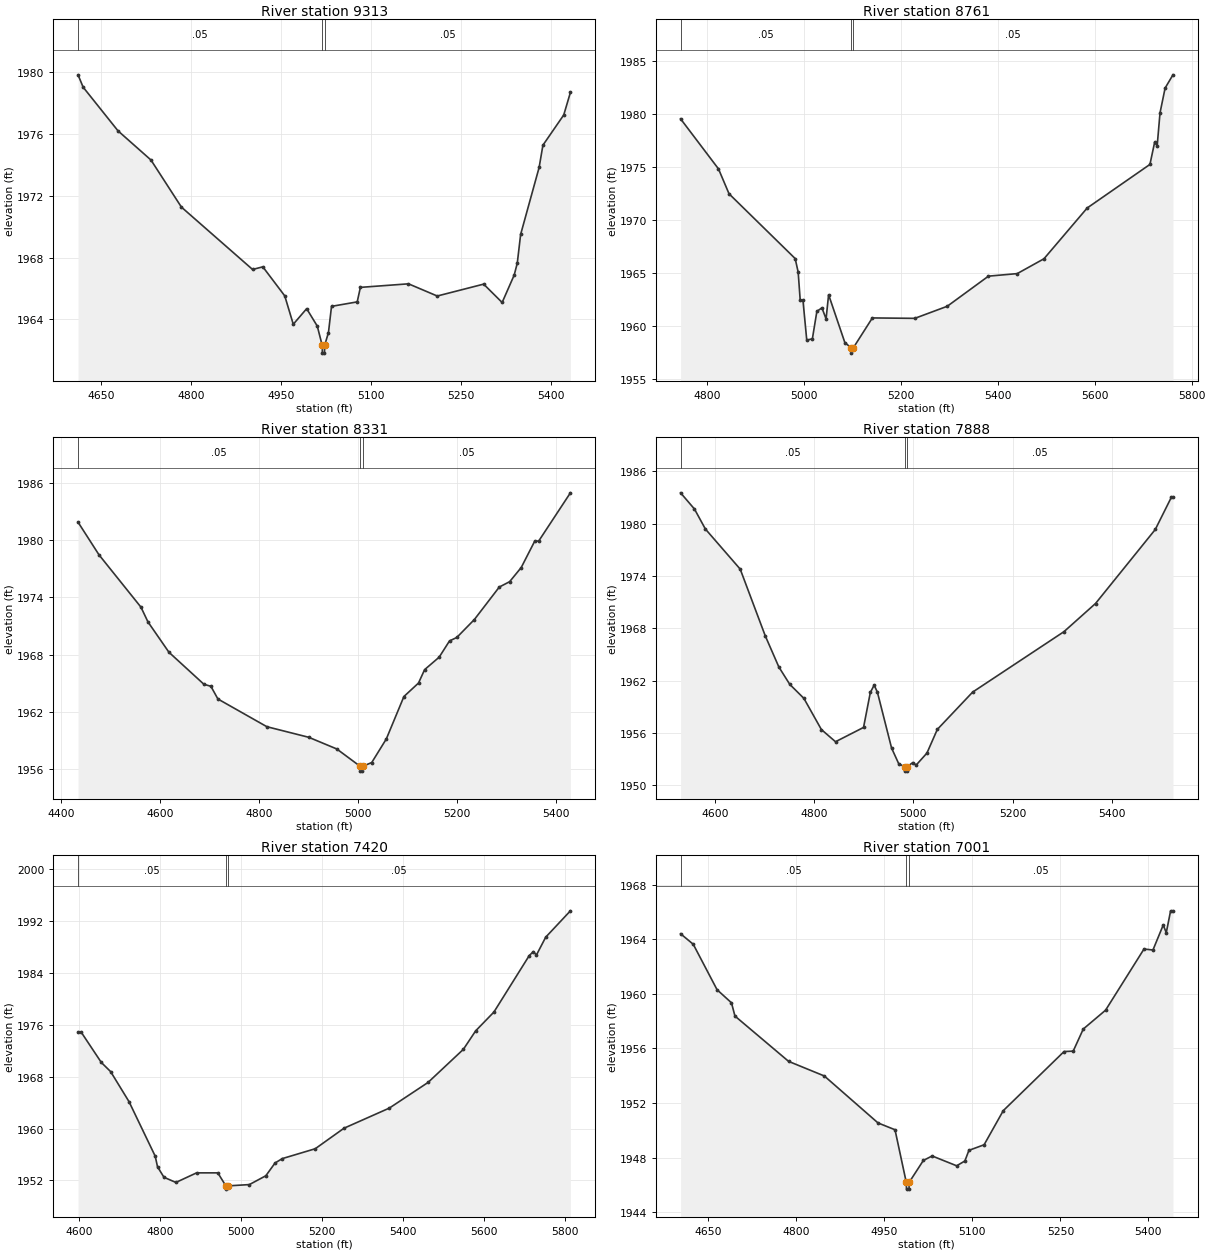
Type RM Length L Ch R = 1,9313,552,552,552
BEGIN DESCRIPTION:
Deadman 62 19.0
END DESCRIPTION:
XS GIS Cut Line= 3
      1648005.04      6838788.02      1648349.48      6838954.49
      1648775.79      6839053.04
#Sta/Elev= 30
  4611.7 1979.84  4620.2 1979.04  4678.3 1976.21  4733.2 1974.32  4783.9 1971.27
  4902.4 1967.23  4919.5 1967.40  4956.0 1965.52  4970.2 1963.68  4992.5 1964.69
  5010.2 1963.56  5018.4 1962.31  5018.7 1961.81  5022.2 1961.81  5022.4 1962.31
  5028.8 1963.14  5033.9 1964.84  5076.7 1965.13  5082.0 1966.07  5162.1 1966.30
  5210.0 1965.51  5287.3 1966.28  5318.1 1965.09  5338.2 1966.87  5343.3 1967.64
  5348.9 1969.50  5379.7 1973.84  5386.0 1975.28  5420.7 1977.24  5431.8 1978.70
#Mann=3,-1,0
  4611.7    0.05       0  5018.4    0.05       0  5022.4    0.05       0
Bank Sta=5018.4,5022.4
Exp/Cntr=0.3,0.1

Type RM Length L Ch R = 1,8761,430,430,430
BEGIN DESCRIPTION:
Deadman 62 18.0
END DESCRIPTION:
XS GIS Cut Line= 3
      1647754.98      6839137.98      1647955.00      6839288.00
      1648690.59      6839502.31
#Sta/Elev= 30
  4745.2 1979.58  4823.4 1974.86  4845.2 1972.51  4981.7 1966.40  4987.9 1965.12
  4992.1 1962.46  4997.8 1962.46  5005.6 1958.71  5017.2 1958.83  5026.5 1961.42
  5036.9 1961.75  5045.5 1960.71  5050.7 1962.99  5084.2 1958.48  5097.1 1957.98
  5097.4 1957.48  5101.7 1957.98  5141.0 1960.80  5228.6 1960.76  5295.6 1961.90
  5380.6 1964.74  5440.0 1964.98  5495.2 1966.38  5584.4 1971.17  5713.9 1975.28
  5723.6 1977.37  5728.8 1977.02  5734.7 1980.14  5745.2 1982.48  5761.4 1983.73
#Mann=3,-1,0
  4745.2    0.05       0  5097.1    0.05       0  5101.7    0.05       0
Bank Sta=5097.1,5101.7
Exp/Cntr=0.3,0.1

Type RM Length L Ch R = 1,8331,443,443,443
BEGIN DESCRIPTION:
Deadman 62 17.0
END DESCRIPTION:
XS GIS Cut Line= 3
      1647554.99      6839287.99      1647955.00      6839688.00
      1648304.99      6839937.99
#Sta/Elev= 30
  4433.7 1981.86  4476.1 1978.44  4561.0 1972.96  4575.1 1971.42  4617.6 1968.24
  4688.3 1964.89  4702.4 1964.68  4716.6 1963.35  4815.6 1960.45  4900.4 1959.34
  4957.0 1958.12  5004.4 1956.30  5004.7 1955.80  5008.8 1955.80  5009.2 1956.30
  5027.7 1956.70  5057.2 1959.17  5092.8 1963.61  5122.3 1965.02  5134.6 1966.42
  5164.1 1967.73  5185.0 1969.43  5199.7 1969.79  5235.3 1971.67  5285.7 1975.07
  5306.6 1975.63  5330.0 1977.11  5357.0 1979.84  5365.6 1979.90  5429.5 1984.93
#Mann=3,-1,0
  4433.7    0.05       0  5004.4    0.05       0  5009.2    0.05       0
Bank Sta=5004.4,5009.2
Exp/Cntr=0.3,0.1

Type RM Length L Ch R = 1,7888,468,468,468
BEGIN DESCRIPTION:
Deadman 62 16.0
END DESCRIPTION:
XS GIS Cut Line= 3
      1647304.97      6839687.98      1647655.00      6839988.00
      1648054.98      6840337.99
#Sta/Elev= 30
  4530.8 1983.55  4558.8 1981.69  4580.8 1979.40  4651.0 1974.80  4701.5 1967.15
  4728.9 1963.58  4750.9 1961.59  4779.4 1959.98  4814.6 1956.41  4843.1 1955.01
  4899.6 1956.65  4913.3 1960.66  4921.0 1961.50  4927.6 1960.68  4956.1 1954.29
  4970.4 1952.50  4982.3 1952.14  4982.6 1951.64  4986.7 1951.64  4987.1 1952.14
  4998.9 1952.62  5005.6 1952.33  5027.4 1953.71  5048.3 1956.42  5119.5 1960.70
  5303.6 1967.63  5367.2 1970.86  5487.7 1979.35  5520.0 1983.03  5523.3 1983.03
#Mann=3,-1,0
  4530.8    0.05       0  4982.3    0.05       0  4987.1    0.05       0
Bank Sta=4982.3,4987.1
Exp/Cntr=0.3,0.1

Type RM Length L Ch R = 1,7420,419,419,419
BEGIN DESCRIPTION:
Deadman 62 15.0
END DESCRIPTION:
XS GIS Cut Line= 3
      1647155.00      6839988.00      1647355.00      6840338.00
      1648155.04      6840488.01
#Sta/Elev= 30
  4597.1 1974.83  4605.0 1974.87  4654.7 1970.20  4677.7 1968.79  4723.1 1964.16
  4787.9 1955.74  4793.6 1954.10  4809.5 1952.49  4839.0 1951.69  4890.1 1953.17
  4942.6 1953.17  4962.5 1951.16  4962.8 1950.66  4967.4 1951.16  5020.6 1951.36
  5061.3 1952.72  5084.2 1954.70  5102.0 1955.37  5183.4 1956.89  5254.6 1960.06
  5366.5 1963.16  5462.3 1967.12  5549.6 1972.23  5580.1 1975.09  5625.1 1977.98
  5712.4 1986.69  5722.6 1987.31  5730.2 1986.78  5753.1 1989.53  5814.2 1993.60
#Mann=3,-1,0
  4597.1    0.05       0  4962.5    0.05       0  4967.4    0.05       0
Bank Sta=4962.5,4967.4
Exp/Cntr=0.3,0.1

Type RM Length L Ch R = 1,7001,482,482,482
BEGIN DESCRIPTION:
Deadman 62 14.0
END DESCRIPTION:
XS GIS Cut Line= 3
      1646934.84      6840146.73      1647005.00      6840538.00
      1647134.31      6840960.65
#Sta/Elev= 30
  4602.4 1964.40  4624.0 1963.63  4664.6 1960.30  4689.2 1959.34  4695.1 1958.37
  4786.6 1955.05  4847.5 1953.98  4939.0 1950.54  4968.0 1950.04  4987.2 1946.19
  4987.6 1945.69  4991.9 1945.69  4992.2 1946.19  5016.3 1947.79  5031.3 1948.12
  5073.1 1947.40  5087.1 1947.75  5094.0 1948.53  5119.9 1948.94  5152.6 1951.44
  5256.2 1955.77  5271.8 1955.80  5289.0 1957.42  5327.0 1958.80  5392.5 1963.28
  5407.8 1963.21  5425.3 1965.04  5430.5 1964.48  5437.9 1966.08  5441.9 1966.08
#Mann=3,-1,0
  4602.4    0.05       0  4987.2    0.05       0  4992.2    0.05       0
Bank Sta=4987.2,4992.2
Exp/Cntr=0.3,0.1

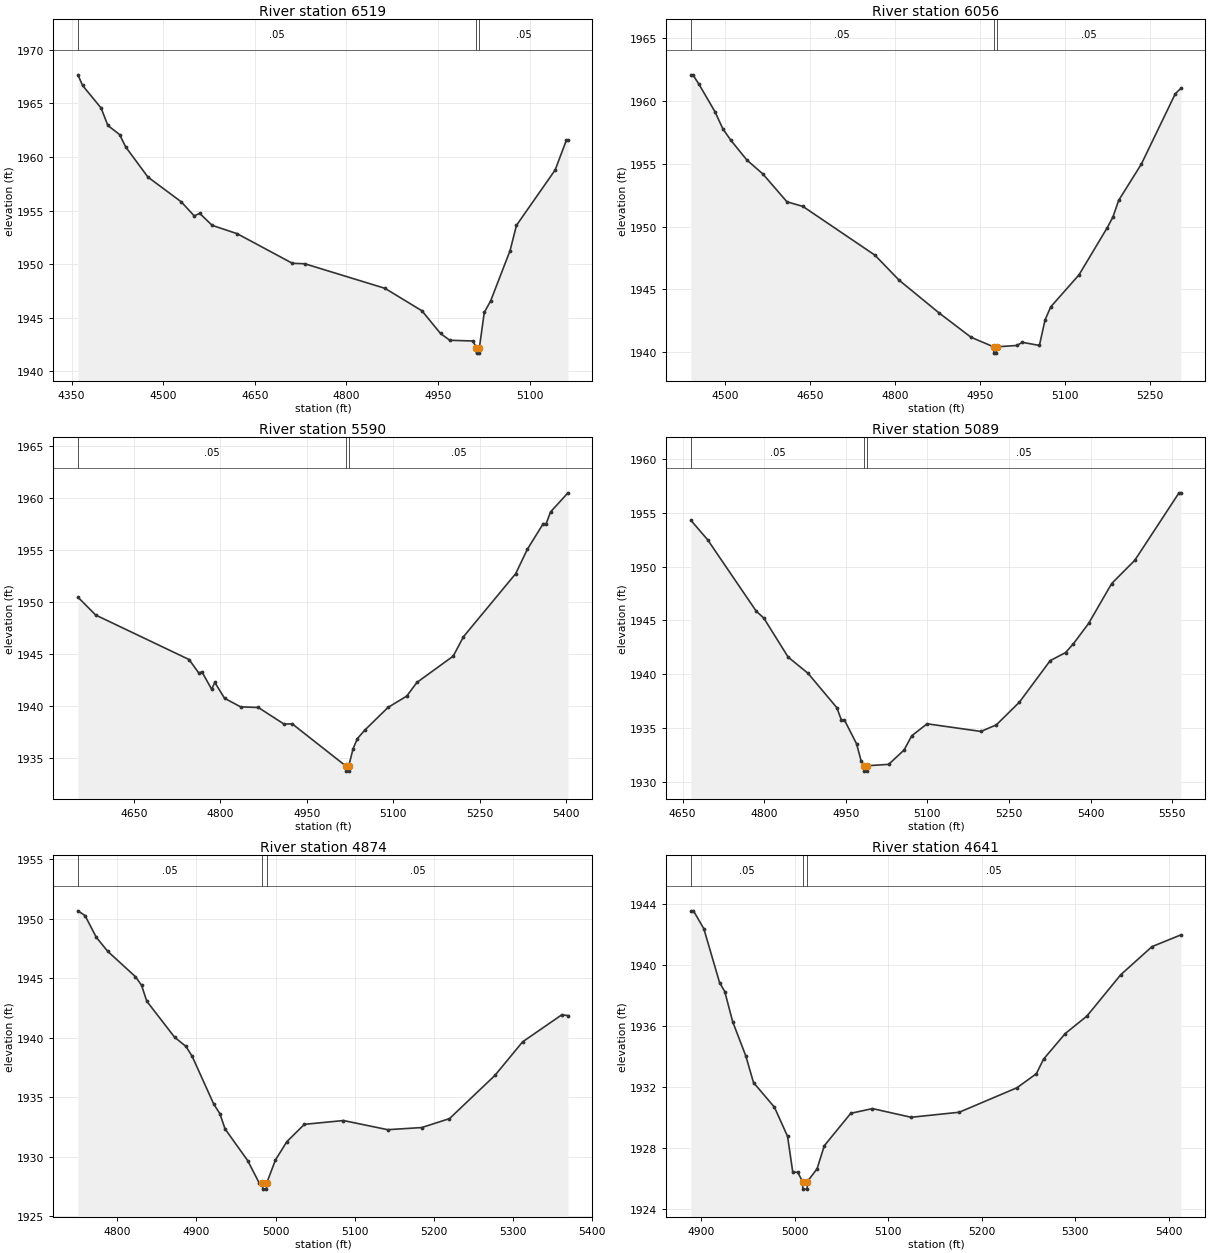
Type RM Length L Ch R = 1,6519,463,463,463
BEGIN DESCRIPTION:
Deadman 62 13.0
END DESCRIPTION:
XS GIS Cut Line= 3
      1646696.39      6840050.48      1646605.00      6840688.00
      1646555.02      6840837.95
#Sta/Elev= 30
  4360.5 1967.65  4368.1 1966.66  4398.4 1964.56  4409.5 1962.93  4428.7 1962.08
  4438.8 1960.92  4475.1 1958.12  4529.7 1955.81  4550.7 1954.51  4560.0 1954.73
  4580.2 1953.62  4621.3 1952.84  4711.6 1950.08  4731.8 1950.04  4863.1 1947.75
  4923.7 1945.65  4954.0 1943.54  4969.2 1942.91  5007.2 1942.84  5012.5 1942.21
  5012.9 1941.71  5017.2 1941.71  5017.6 1942.21  5025.6 1945.50  5036.2 1946.60
  5067.8 1951.26  5078.3 1953.62  5141.6 1958.78  5160.0 1961.55  5162.6 1961.55
#Mann=3,-1,0
  4360.5    0.05       0  5012.5    0.05       0  5017.6    0.05       0
Bank Sta=5012.5,5017.6
Exp/Cntr=0.3,0.1

Type RM Length L Ch R = 1,6056,466,466,466
BEGIN DESCRIPTION:
Deadman 62 12.0
END DESCRIPTION:
XS GIS Cut Line= 3
      1646605.01      6840087.99      1646205.00      6840488.00
      1646205.00      6840787.99
#Sta/Elev= 30
  4439.6 1962.07  4443.2 1962.07  4453.8 1961.33  4482.0 1959.15  4496.2 1957.77
  4510.3 1956.86  4538.6 1955.29  4566.9 1954.18  4609.3 1951.97  4637.6 1951.60
  4764.9 1947.72  4807.3 1945.74  4878.0 1943.13  4934.6 1941.19  4974.5 1940.43
  4974.9 1939.93  4979.2 1939.93  4979.6 1940.43  5015.3 1940.54  5025.3 1940.79
  5055.3 1940.54  5065.3 1942.57  5075.3 1943.61  5125.3 1946.16  5175.3 1949.92
  5185.3 1950.77  5195.3 1952.08  5235.3 1954.96  5295.3 1960.56  5305.3 1961.00
#Mann=3,-1,0
  4439.6    0.05       0  4974.5    0.05       0  4979.6    0.05       0
Bank Sta=4974.5,4979.6
Exp/Cntr=0.3,0.1

Type RM Length L Ch R = 1,5590,501,501,501
BEGIN DESCRIPTION:
Deadman 62 11.0
END DESCRIPTION:
XS GIS Cut Line= 3
      1646005.02      6839987.97      1645805.00      6840388.00
      1645855.00      6840788.03
#Sta/Elev= 30
  4553.0 1950.44  4583.8 1948.72  4745.9 1944.44  4762.7 1943.15  4768.3 1943.25
  4785.0 1941.59  4790.6 1942.24  4807.4 1940.72  4835.3 1939.89  4866.1 1939.83
  4910.8 1938.23  4924.8 1938.26  5017.8 1934.21  5018.2 1933.71  5022.6 1933.71
  5023.0 1934.21  5030.5 1935.87  5038.0 1936.84  5050.6 1937.64  5091.0 1939.83
  5123.7 1940.93  5141.3 1942.24  5204.3 1944.77  5222.0 1946.63  5312.7 1952.70
  5332.8 1955.03  5360.5 1957.51  5365.6 1957.50  5373.1 1958.63  5403.4 1960.47
#Mann=3,-1,0
  4553.0    0.05       0  5017.8    0.05       0  5023.0    0.05       0
Bank Sta=5017.8,5023
Exp/Cntr=0.3,0.1

Type RM Length L Ch R = 1,5089,215,215,215
BEGIN DESCRIPTION:
Deadman 62 10.0
END DESCRIPTION:
XS GIS Cut Line= 3
      1645154.99      6840087.97      1645305.00      6840388.00
      1645704.98      6840787.98
#Sta/Elev= 30
  4665.1 1954.30  4695.9 1952.49  4785.3 1945.85  4799.3 1945.20  4844.0 1941.58
  4880.4 1940.08  4933.5 1936.88  4941.8 1935.74  4947.4 1935.74  4969.8 1933.52
  4978.2 1931.93  4983.9 1931.48  4984.3 1930.98  4988.8 1930.98  4989.2 1931.48
  5028.8 1931.61  5057.1 1932.94  5071.3 1934.27  5099.5 1935.38  5198.5 1934.67
  5226.8 1935.28  5269.2 1937.39  5325.8 1941.25  5354.1 1942.00  5368.2 1942.80
  5396.5 1944.71  5438.9 1948.42  5481.4 1950.58  5562.7 1956.85  5566.2 1956.85
#Mann=3,-1,0
  4665.1    0.05       0  4983.9    0.05       0  4989.2    0.05       0
Bank Sta=4983.9,4989.2
Exp/Cntr=0.3,0.1

Type RM Length L Ch R = 1,4874,233,233,233
BEGIN DESCRIPTION:
Mapping XS db7c14fa
END DESCRIPTION:
XS GIS Cut Line= 2
      1644942.91      6840347.44      1645420.90      6840742.31
#Sta/Elev= 30
  4750.0 1950.67  4759.0 1950.27  4773.3 1948.44  4787.6 1947.27  4822.8 1945.13
  4830.5 1944.41  4837.1 1943.07  4872.3 1940.04  4886.6 1939.27  4894.5 1938.44
  4921.8 1934.42  4929.6 1933.61  4936.1 1932.33  4964.8 1929.66  4979.1 1927.81
  4983.5 1927.76  4983.9 1927.26  4988.4 1927.26  4988.8 1927.76  4999.9 1929.71
  5014.3 1931.25  5036.5 1932.71  5086.0 1933.03  5141.9 1932.26  5185.0 1932.44
  5220.1 1933.19  5277.5 1936.82  5312.6 1939.65  5362.3 1941.93  5370.0 1941.86
#Mann=3,-1,0
  4750.0    0.05       0  4983.5    0.05       0  4988.8    0.05       0
Bank Sta=4983.5,4988.8
Exp/Cntr=0.3,0.1

Type RM Length L Ch R = 1,4641,299,299,299
BEGIN DESCRIPTION:
Deadman 62 9.0
END DESCRIPTION:
XS GIS Cut Line= 3
      1644905.03      6840638.01      1645005.00      6840688.00
      1645405.02      6840788.00
#Sta/Elev= 30
  4888.8 1943.57  4891.6 1943.57  4902.7 1942.39  4919.5 1938.86  4925.1 1938.26
  4933.5 1936.29  4947.5 1934.05  4955.8 1932.29  4978.2 1930.67  4992.2 1928.76
  4997.8 1926.40  5003.1 1926.40  5008.2 1925.79  5008.6 1925.29  5013.1 1925.29
  5013.5 1925.79  5023.8 1926.63  5031.5 1928.14  5059.8 1930.27  5083.0 1930.58
  5124.3 1930.01  5175.8 1930.34  5237.6 1931.95  5258.3 1932.87  5266.0 1933.83
  5289.2 1935.51  5312.4 1936.66  5348.5 1939.37  5382.0 1941.22  5412.9 1941.99
#Mann=3,-1,0
  4888.8    0.05       0  5008.2    0.05       0  5013.5    0.05       0
Bank Sta=5008.2,5013.5
Exp/Cntr=0.3,0.1

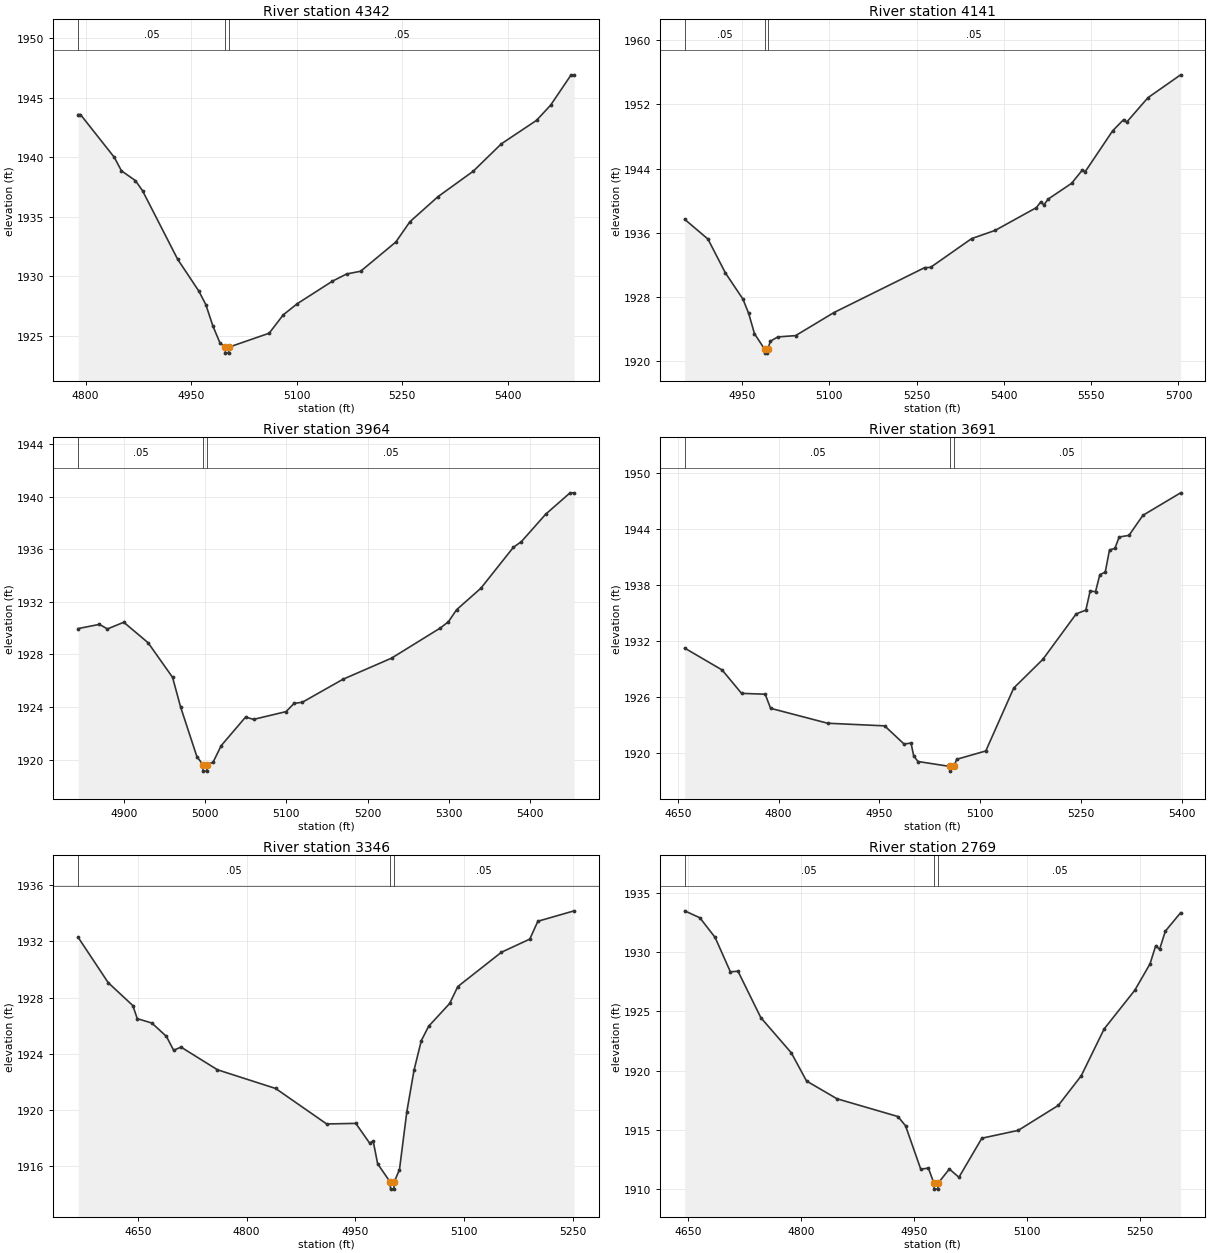
Type RM Length L Ch R = 1,4342,201,201,201
BEGIN DESCRIPTION:
Mapping XS c6fefbfe
END DESCRIPTION:
XS GIS Cut Line= 2
      1644793.60      6840988.07      1645498.49      6840984.60
#Sta/Elev= 30
  4789.5 1943.58  4792.7 1943.58  4840.9 1939.98  4850.9 1938.86  4870.9 1938.03
  4880.9 1937.19  4930.9 1931.43  4960.9 1928.77  4970.9 1927.63  4980.9 1925.84
  4990.9 1924.43  4998.3 1924.06  4998.7 1923.56  5003.2 1923.56  5003.6 1924.06
  5060.9 1925.23  5080.9 1926.77  5100.9 1927.71  5150.9 1929.60  5170.9 1930.20
  5190.9 1930.43  5240.9 1932.88  5260.9 1934.58  5300.9 1936.69  5350.9 1938.82
  5390.9 1941.12  5440.9 1943.09  5460.9 1944.36  5490.1 1946.91  5494.4 1946.91
#Mann=3,-1,0
  4789.5    0.05       0  4998.3    0.05       0  5003.6    0.05       0
Bank Sta=4998.3,5003.6
Exp/Cntr=0.3,0.1

Type RM Length L Ch R = 1,4141,177,177,177
BEGIN DESCRIPTION:
Deadman 62 8.0
END DESCRIPTION:
XS GIS Cut Line= 3
      1644855.03      6841188.00      1645005.00      6841188.00
      1645700.65      6841286.14
#Sta/Elev= 30
  4851.2 1937.69  4891.2 1935.23  4921.2 1931.01  4951.2 1927.77  4961.2 1925.97
  4971.2 1923.44  4988.5 1921.52  4988.9 1921.02  4993.4 1921.02  4993.9 1921.52
  4998.7 1922.51  5011.3 1923.04  5041.8 1923.20  5107.9 1926.08  5263.7 1931.67
  5273.8 1931.70  5344.5 1935.29  5384.9 1936.31  5455.6 1939.14  5463.6 1939.88
  5468.6 1939.47  5475.8 1940.20  5516.2 1942.17  5534.7 1943.82  5539.8 1943.64
  5586.9 1948.72  5605.8 1950.12  5610.9 1949.79  5647.5 1952.84  5703.7 1955.69
#Mann=3,-1,0
  4851.2    0.05       0  4988.5    0.05       0  4993.9    0.05       0
Bank Sta=4988.5,4993.9
Exp/Cntr=0.3,0.1

Type RM Length L Ch R = 1,3964,273,273,273
BEGIN DESCRIPTION:
Mapping XS 02e2c4b7
END DESCRIPTION:
XS GIS Cut Line= 2
      1644798.81      6841354.39      1645409.96      6841333.56
#Sta/Elev= 30
  4843.3 1929.97  4869.5 1930.29  4879.3 1929.94  4899.5 1930.45  4929.5 1928.89
  4959.6 1926.26  4969.6 1923.99  4989.6 1920.23  4996.9 1919.62  4997.3 1919.12
  5001.9 1919.12  5002.3 1919.62  5009.6 1919.80  5019.6 1921.06  5049.6 1923.23
  5059.6 1923.06  5099.6 1923.65  5109.6 1924.28  5119.6 1924.36  5169.7 1926.11
  5229.7 1927.72  5289.7 1930.01  5299.8 1930.49  5309.8 1931.40  5339.8 1933.04
  5379.8 1936.15  5389.8 1936.59  5419.8 1938.68  5449.8 1940.30  5454.8 1940.30
#Mann=3,-1,0
  4843.3    0.05       0  4996.9    0.05       0  5002.3    0.05       0
Bank Sta=4996.9,5002.3
Exp/Cntr=0.3,0.1

Type RM Length L Ch R = 1,3691,345,345,345
BEGIN DESCRIPTION:
Deadman 62 7.0
END DESCRIPTION:
XS GIS Cut Line= 3
      1644646.66      6841327.52      1644855.00      6841588.00
      1645170.87      6841840.43
#Sta/Elev= 30
  4660.2 1931.23  4716.0 1928.88  4744.8 1926.38  4780.0 1926.29  4788.0 1924.78
  4872.9 1923.18  4957.7 1922.90  4986.5 1920.96  4997.0 1921.05  5001.0 1919.67
  5007.4 1919.08  5055.1 1918.55  5055.5 1918.05  5060.5 1918.55  5065.0 1919.32
  5108.2 1920.21  5149.8 1926.95  5193.1 1930.02  5242.7 1934.89  5257.1 1935.30
  5263.5 1937.35  5271.5 1937.27  5277.9 1939.10  5285.9 1939.36  5292.3 1941.74
  5300.3 1941.91  5306.7 1943.13  5321.2 1943.30  5342.0 1945.45  5398.1 1947.86
#Mann=3,-1,0
  4660.2    0.05       0  5055.1    0.05       0  5060.5    0.05       0
Bank Sta=5055.1,5060.5
Exp/Cntr=0.3,0.1

Type RM Length L Ch R = 1,3346,577,577,577
BEGIN DESCRIPTION:
Deadman 62 6.0
END DESCRIPTION:
XS GIS Cut Line= 2
      1644573.28      6841306.90      1644635.18      6841987.79
#Sta/Elev= 30
  4567.9 1932.27  4609.2 1929.06  4643.2 1927.43  4649.3 1926.50  4669.4 1926.19
  4689.5 1925.24  4699.5 1924.25  4709.6 1924.48  4759.8 1922.87  4840.1 1921.54
  4910.4 1919.02  4950.6 1919.06  4969.5 1917.67  4974.6 1917.79  4980.7 1916.19
  4998.0 1914.89  4998.5 1914.39  5003.1 1914.39  5003.5 1914.89  5010.8 1915.78
  5020.9 1919.88  5030.9 1922.85  5040.9 1924.94  5051.0 1925.96  5080.0 1927.58
  5091.2 1928.78  5151.4 1931.22  5190.4 1932.15  5201.6 1933.42  5251.6 1934.16
#Mann=3,-1,0
  4567.9    0.05       0  4998.0    0.05       0  5003.5    0.05       0
Bank Sta=4998,5003.5
Exp/Cntr=0.3,0.1

Type RM Length L Ch R = 1,2769,190,190,190
BEGIN DESCRIPTION:
Deadman 62 5.0
END DESCRIPTION:
XS GIS Cut Line= 3
      1644155.00      6841388.01      1644105.00      6841738.00
      1644155.00      6842038.02
#Sta/Elev= 30
  4646.0 1933.50  4666.2 1932.91  4686.4 1931.25  4706.6 1928.35  4716.7 1928.40
  4747.0 1924.48  4787.4 1921.51  4807.6 1919.13  4848.0 1917.63  4928.8 1916.13
  4938.9 1915.35  4959.1 1911.68  4969.2 1911.78  4976.5 1910.50  4977.0 1910.00
  4981.7 1910.00  4982.1 1910.50  4997.0 1911.70  5009.7 1911.00  5040.1 1914.30
  5088.3 1914.96  5141.5 1917.07  5171.9 1919.57  5202.3 1923.53  5242.9 1926.79
  5263.1 1929.02  5270.7 1930.56  5275.8 1930.24  5283.4 1931.78  5303.7 1933.34
#Mann=3,-1,0
  4646.0    0.05       0  4976.5    0.03       0  4982.1    0.05       0
Bank Sta=4976.5,4982.1
Exp/Cntr=0.3,0.1

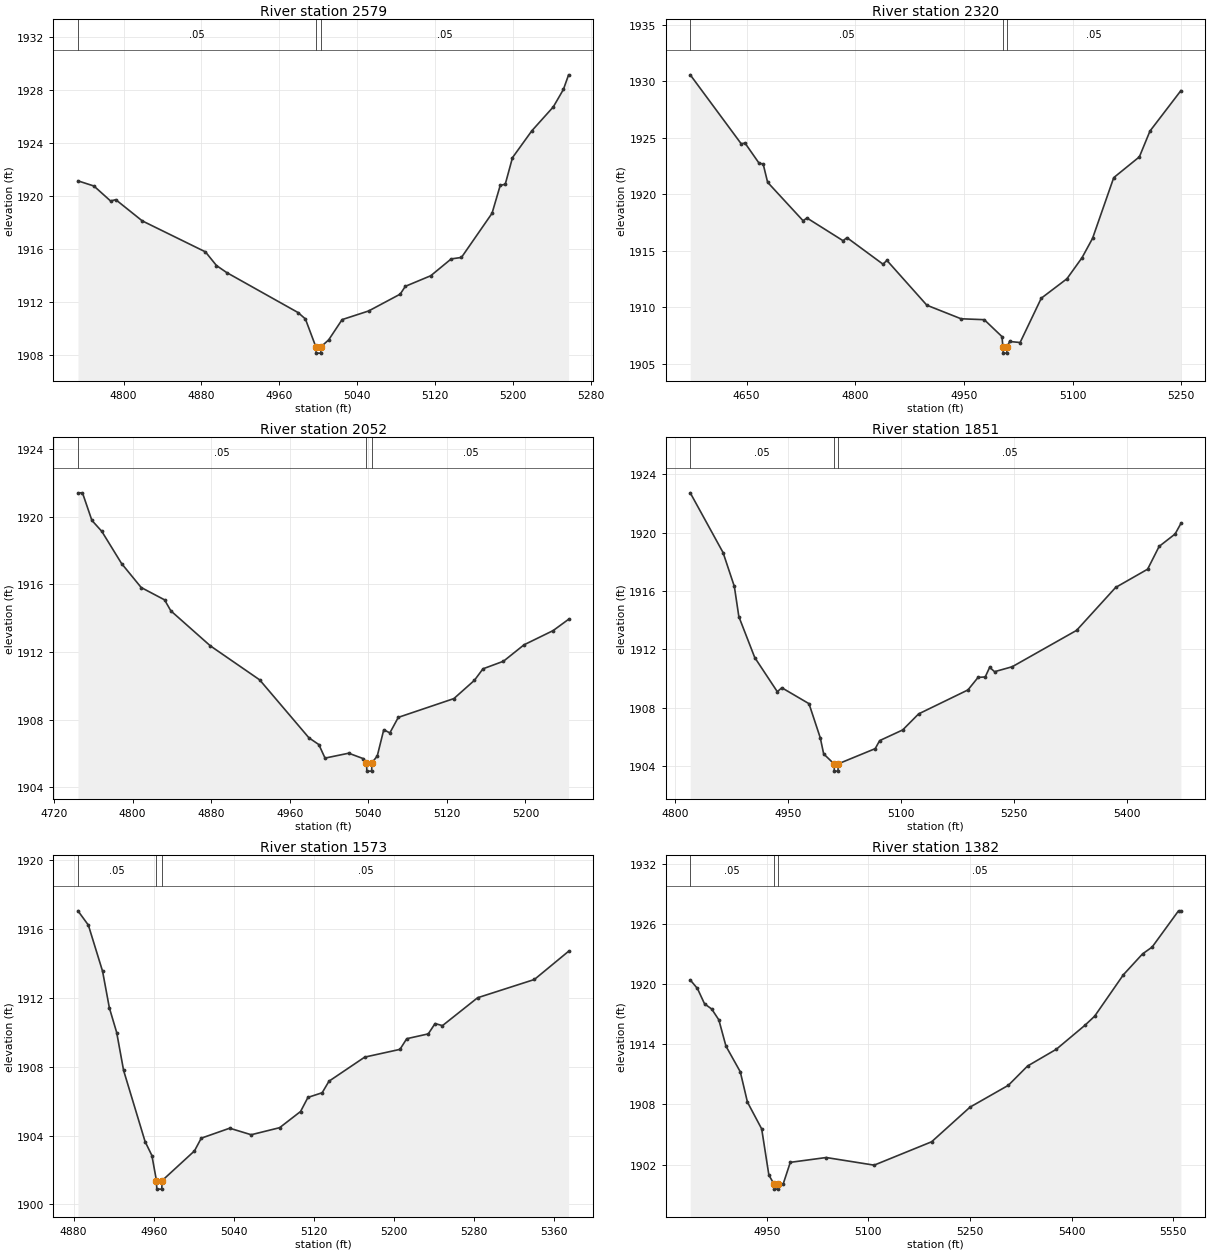
Type RM Length L Ch R = 1,2579,259,259,259
BEGIN DESCRIPTION:
Mapping XS 5dc34d57
END DESCRIPTION:
XS GIS Cut Line= 2
      1643859.58      6841552.30      1644010.02      6842033.01
#Sta/Elev= 30
  4753.2 1921.13  4769.6 1920.74  4786.7 1919.61  4792.0 1919.71  4819.2 1918.11
  4884.1 1915.77  4895.4 1914.74  4905.9 1914.21  4979.2 1911.19  4986.7 1910.71
  4997.3 1908.63  4997.8 1908.13  5002.5 1908.13  5003.0 1908.63  5010.6 1909.13
  5024.4 1910.66  5051.6 1911.31  5084.0 1912.58  5089.3 1913.17  5115.4 1913.97
  5136.4 1915.24  5146.9 1915.35  5178.3 1918.68  5186.7 1920.78  5191.9 1920.88
  5199.3 1922.88  5219.2 1924.91  5241.2 1926.71  5251.6 1928.03  5256.9 1929.13
#Mann=3,-1,0
  4753.2    0.05       0  4997.3    0.05       0  5003.0    0.05       0
Bank Sta=4997.3,5003
Exp/Cntr=0.3,0.1

Type RM Length L Ch R = 1,2320,268,268,268
BEGIN DESCRIPTION:
Deadman 62 4.0
END DESCRIPTION:
XS GIS Cut Line= 3
      1643555.00      6841488.00      1643705.00      6841888.00
      1643855.00      6842088.00
#Sta/Elev= 30
  4572.3 1930.57  4642.6 1924.47  4647.9 1924.53  4667.5 1922.73  4672.9 1922.69
  4679.1 1921.06  4728.0 1917.66  4733.4 1917.90  4783.2 1915.89  4788.6 1916.16
  4838.4 1913.81  4843.7 1914.15  4898.9 1910.18  4946.1 1908.98  4978.1 1908.90
  5002.6 1907.40  5003.9 1906.44  5004.4 1905.94  5009.2 1905.94  5009.6 1906.44
  5013.0 1906.97  5027.6 1906.88  5056.8 1910.80  5092.2 1912.52  5113.0 1914.38
  5127.6 1916.10  5156.8 1921.47  5192.2 1923.31  5206.8 1925.59  5249.5 1929.17
#Mann=3,-1,0
  4572.3    0.05       0  5003.9    0.05       0  5009.6    0.05       0
Bank Sta=5003.9,5009.6
Exp/Cntr=0.3,0.1

Type RM Length L Ch R = 1,2052,201,201,201
BEGIN DESCRIPTION:
Mapping XS 5e8c98ed
END DESCRIPTION:
XS GIS Cut Line= 3
      1643411.66      6841633.85      1643435.97      6841885.64
      1643578.34      6842087.04
#Sta/Elev= 30
  4744.4 1921.42  4749.0 1921.42  4758.6 1919.79  4768.7 1919.14  4788.8 1917.24
  4808.8 1915.82  4832.6 1915.09  4839.0 1914.44  4879.2 1912.37  4929.4 1910.36
  4979.6 1906.93  4989.7 1906.53  4996.0 1905.73  5020.1 1906.02  5034.9 1905.70
  5038.2 1905.46  5038.6 1904.96  5043.4 1904.96  5043.9 1905.46  5049.2 1905.86
  5055.8 1907.41  5062.0 1907.22  5070.6 1908.14  5127.2 1909.25  5148.1 1910.33
  5156.8 1911.01  5177.7 1911.46  5198.6 1912.43  5228.2 1913.27  5244.0 1913.94
#Mann=3,-1,0
  4744.4    0.05       0  5038.2    0.05       0  5043.9    0.05       0
Bank Sta=5038.2,5043.9
Exp/Cntr=0.3,0.1

Type RM Length L Ch R = 1,1851,278,278,278
BEGIN DESCRIPTION:
Deadman 62 3.0
END DESCRIPTION:
XS GIS Cut Line= 3
      1643154.98      6841787.98      1643255.00      6841938.00
      1643655.00      6842188.00
#Sta/Elev= 30
  4820.1 1922.72  4863.7 1918.63  4878.7 1916.31  4884.7 1914.24  4905.8 1911.44
  4935.8 1909.10  4941.8 1909.37  4977.9 1908.28  4992.9 1905.94  4997.4 1904.84
  5011.1 1904.16  5011.6 1903.66  5016.4 1903.66  5016.8 1904.16  5065.9 1905.20
  5071.8 1905.75  5102.4 1906.48  5123.6 1907.58  5189.1 1909.22  5202.6 1910.08
  5212.1 1910.11  5218.0 1910.77  5224.5 1910.47  5248.0 1910.81  5333.5 1913.30
  5385.4 1916.24  5427.9 1917.49  5443.2 1919.05  5464.4 1919.90  5472.1 1920.62
#Mann=3,-1,0
  4820.1    0.05       0  5011.1    0.05       0  5016.8    0.05       0
Bank Sta=5011.1,5016.8
Exp/Cntr=0.3,0.1

Type RM Length L Ch R = 1,1573,191,191,191
BEGIN DESCRIPTION:
Mapping XS a342dbd9
END DESCRIPTION:
XS GIS Cut Line= 2
      1643010.59      6842067.90      1643343.95      6842427.30
#Sta/Elev= 30
  4884.3 1917.06  4894.7 1916.23  4908.9 1913.55  4915.7 1911.42  4923.0 1909.99
  4929.9 1907.79  4951.4 1903.65  4958.2 1902.84  4962.7 1901.39  4963.1 1900.89
  4968.0 1900.89  4968.5 1901.39  5000.7 1903.11  5007.5 1903.85  5035.9 1904.43
  5057.4 1904.05  5085.8 1904.46  5106.7 1905.40  5114.1 1906.22  5128.3 1906.49
  5135.1 1907.16  5170.8 1908.56  5206.0 1909.01  5212.8 1909.63  5234.3 1909.91
  5241.1 1910.51  5248.5 1910.39  5283.6 1912.01  5340.3 1913.07  5374.5 1914.71
#Mann=3,-1,0
  4884.3    0.05       0  4962.7    0.05       0  4968.5    0.05       0
Bank Sta=4962.7,4968.5
Exp/Cntr=0.3,0.1

Type RM Length L Ch R = 1,1382,403,403,403
BEGIN DESCRIPTION:
Deadman 62 2.0
END DESCRIPTION:
XS GIS Cut Line= 3
      1642904.99      6842137.97      1642955.00      6842288.00
      1643354.98      6842687.98
#Sta/Elev= 30
  4837.2 1920.40  4847.8 1919.55  4858.3 1918.02  4868.9 1917.50  4879.4 1916.42
  4889.9 1913.80  4911.0 1911.25  4921.6 1908.22  4942.6 1905.55  4953.2 1900.95
  4960.8 1900.05  4961.3 1899.55  4966.2 1899.55  4966.6 1900.05  4974.3 1900.06
  4984.8 1902.22  5037.8 1902.70  5108.5 1901.94  5193.3 1904.27  5249.9 1907.72
  5306.5 1909.90  5334.8 1911.82  5377.2 1913.49  5419.6 1915.89  5433.8 1916.79
  5476.2 1920.92  5504.5 1923.00  5518.6 1923.68  5557.5 1927.29  5561.0 1927.29
#Mann=3,-1,0
  4837.2    0.05       0  4960.8    0.05       0  4966.6    0.05       0
Bank Sta=4960.8,4966.6
Exp/Cntr=0.3,0.1

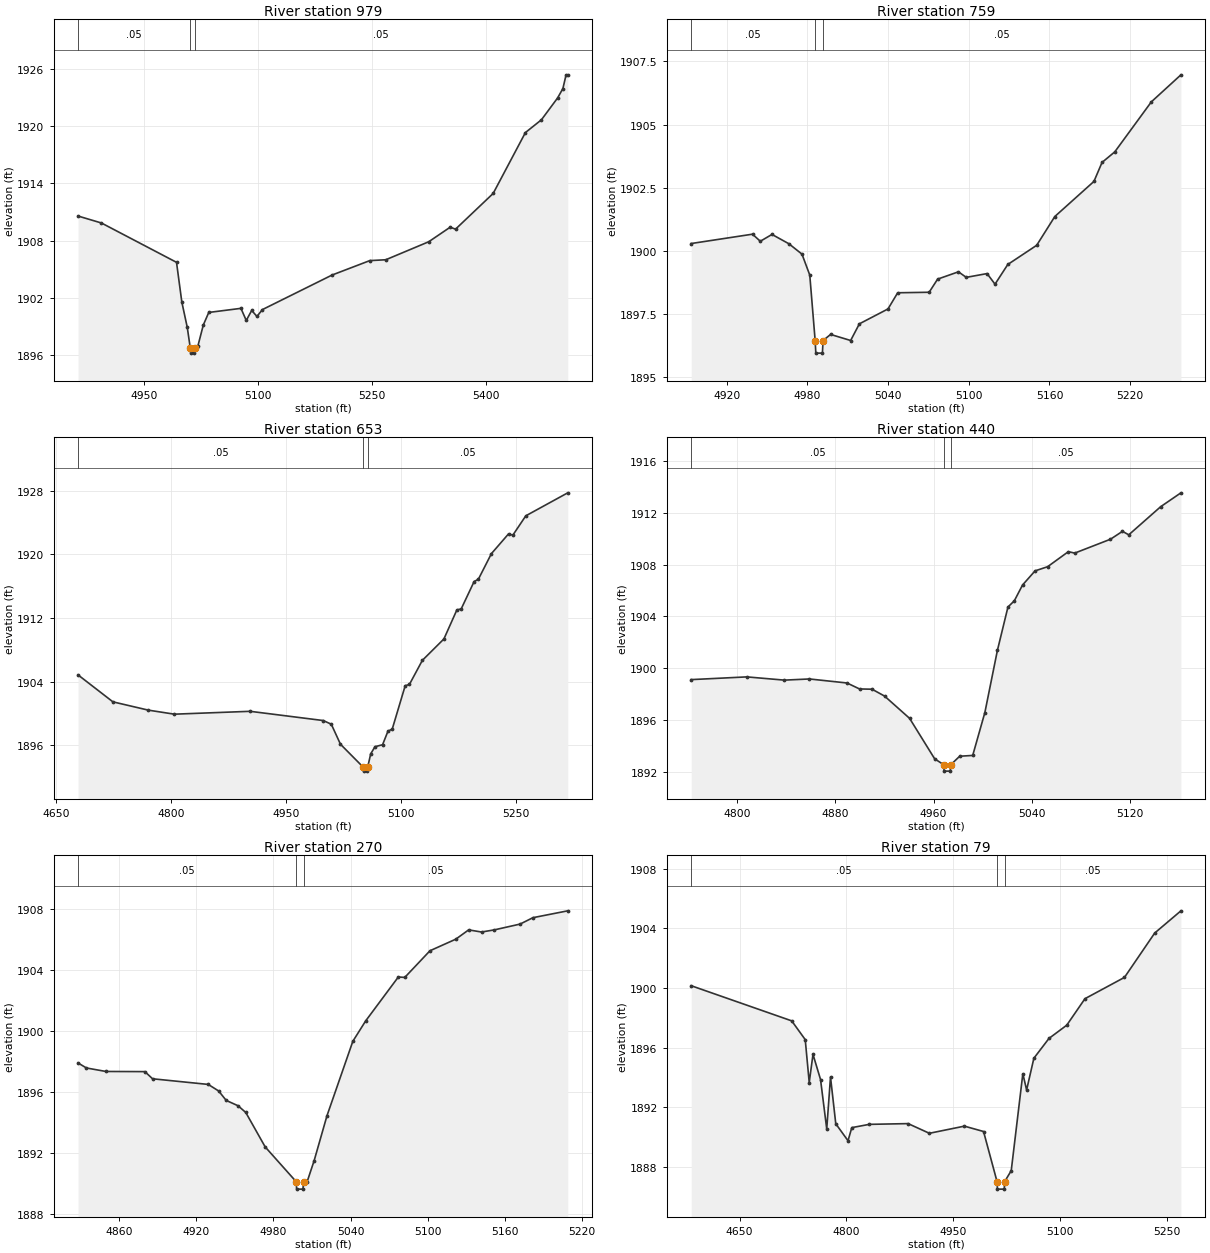
Type RM Length L Ch R = 1,979,220,220,220
BEGIN DESCRIPTION:
Mapping XS 65610066
END DESCRIPTION:
XS GIS Cut Line= 2
      1642658.79      6842370.69      1643105.89      6842836.14
#Sta/Elev= 30
  4862.7 1910.57  4893.5 1909.84  4992.5 1905.71  4999.5 1901.54  5006.7 1898.87
  5010.7 1896.68  5011.2 1896.18  5016.1 1896.18  5016.6 1896.68  5020.8 1896.97
  5027.8 1899.13  5035.0 1900.45  5077.4 1900.88  5084.4 1899.61  5091.6 1900.66
  5098.5 1900.03  5105.7 1900.75  5197.6 1904.38  5247.2 1905.89  5268.3 1905.98
  5324.9 1907.87  5353.2 1909.40  5360.2 1909.19  5409.8 1912.94  5452.3 1919.33
  5473.4 1920.67  5494.7 1922.96  5501.7 1923.95  5505.9 1925.39  5508.1 1925.39
#Mann=3,-1,0
  4862.7    0.05       0  5010.7    0.05       0  5016.6    0.05       0
Bank Sta=5010.7,5016.6
Exp/Cntr=0.3,0.1

Type RM Length L Ch R = 1,759,106,106,106
BEGIN DESCRIPTION:
Mapping XS c5ec8493
END DESCRIPTION:
XS GIS Cut Line= 2
      1642563.58      6842597.86      1642875.20      6842786.55
#Sta/Elev= 30
  4893.5 1900.29  4939.1 1900.66  4944.9 1900.38  4953.6 1900.65  4966.2 1900.28
  4975.9 1899.87  4981.7 1899.04  4985.7 1896.45  4986.2 1895.95  4991.1 1895.95
  4991.6 1896.45  4997.2 1896.69  5012.1 1896.45  5018.6 1897.11  5039.9 1897.70
  5047.1 1898.34  5070.5 1898.36  5076.8 1898.88  5092.3 1899.17  5098.1 1898.95
  5113.6 1899.10  5119.5 1898.68  5129.0 1899.46  5150.5 1900.22  5164.0 1901.36
  5193.1 1902.75  5199.1 1903.50  5208.6 1903.92  5235.8 1905.90  5257.8 1906.97
#Mann=3,-1,0
  4893.5    0.05       0  4985.7    0.05       0  4991.6    0.05       0
Bank Sta=4985.7,4991.6
Exp/Cntr=0.3,0.1

Type RM Length L Ch R = 1,653,213,213,213
BEGIN DESCRIPTION:
Mapping XS 825bfd74
END DESCRIPTION:
XS GIS Cut Line= 3
      1642555.64      6842432.58      1642544.18      6842620.63
      1642742.81      6843024.76
#Sta/Elev= 30
  4679.1 1904.84  4724.6 1901.45  4770.7 1900.41  4804.7 1899.90  4903.5 1900.26
  4998.9 1899.10  5009.4 1898.64  5021.4 1896.12  5051.0 1893.24  5051.5 1892.74
  5056.4 1892.74  5056.9 1893.24  5060.8 1894.91  5066.4 1895.81  5076.3 1896.06
  5083.3 1897.76  5088.9 1898.03  5105.8 1903.48  5111.3 1903.64  5128.2 1906.67
  5156.3 1909.36  5173.2 1913.01  5178.8 1913.13  5195.7 1916.58  5201.2 1916.86
  5218.2 1920.08  5240.6 1922.57  5246.2 1922.41  5263.1 1924.84  5317.8 1927.73
#Mann=3,-1,0
  4679.1    0.05       0  5051.0    0.05       0  5056.9    0.05       0
Bank Sta=5051,5056.9
Exp/Cntr=0.3,0.1

Type RM Length L Ch R = 1,440,170,170,170
BEGIN DESCRIPTION:
Mapping XS 3c849cfa
END DESCRIPTION:
XS GIS Cut Line= 3
      1642482.15      6842583.57      1642437.84      6842803.69
      1642400.92      6842974.10
#Sta/Elev= 30
  4762.6 1899.12  4807.9 1899.33  4838.5 1899.08  4858.9 1899.17  4889.5 1898.86
  4899.7 1898.40  4909.9 1898.38  4920.1 1897.85  4940.5 1896.13  4960.9 1893.01
  4968.2 1892.56  4968.7 1892.06  4973.6 1892.06  4974.1 1892.56  4981.3 1893.21
  4991.9 1893.27  5001.8 1896.58  5012.0 1901.37  5020.6 1904.72  5025.8 1905.20
  5032.5 1906.42  5042.7 1907.51  5052.9 1907.83  5069.8 1908.99  5075.0 1908.88
  5104.1 1909.95  5113.9 1910.56  5119.0 1910.29  5145.0 1912.46  5161.5 1913.53
#Mann=3,-1,0
  4762.6    0.05       0  4968.2    0.05       0  4974.1    0.05       0
Bank Sta=4968.2,4974.1
Exp/Cntr=0.3,0.1

Type RM Length L Ch R = 1,270,191,191,191
BEGIN DESCRIPTION:
Mapping XS d995a1c7
END DESCRIPTION:
XS GIS Cut Line= 3
      1642390.60      6842582.94      1642293.68      6842732.55
      1642283.24      6842935.02
#Sta/Elev= 30
  4828.0 1897.92  4834.5 1897.59  4849.7 1897.36  4880.0 1897.35  4886.0 1896.88
  4929.3 1896.51  4937.4 1896.08  4943.3 1895.46  4952.5 1895.11  4958.5 1894.67
  4973.6 1892.41  4997.6 1890.14  4998.1 1889.64  5003.0 1889.64  5003.5 1890.14
  5006.3 1890.14  5011.7 1891.51  5021.7 1894.46  5041.8 1899.34  5051.8 1900.68
  5077.2 1903.56  5082.2 1903.53  5101.8 1905.28  5121.9 1906.04  5131.9 1906.65
  5141.9 1906.51  5151.9 1906.65  5171.9 1907.03  5181.9 1907.45  5209.0 1907.90
#Mann=3,-1,0
  4828.0    0.05       0  4997.6    0.05       0  5003.5    0.05       0
Bank Sta=4997.6,5003.5
Exp/Cntr=0.3,0.1

Type RM Length L Ch R = 1,79,0,0,0
BEGIN DESCRIPTION:
Deadman 62 1.0
END DESCRIPTION:
XS GIS Cut Line= 3
      1642514.41      6842483.05      1642131.41      6842631.39
      1642224.13      6842892.70
#Sta/Elev= 30
  4582.1 1900.15  4723.3 1897.79  4742.3 1896.53  4747.9 1893.65  4753.2 1895.54
  4763.8 1893.85  4772.5 1890.53  4777.8 1894.02  4785.2 1890.88  4802.4 1889.74
  4807.7 1890.62  4832.3 1890.84  4886.8 1890.89  4916.7 1890.24  4965.9 1890.72
  4992.8 1890.36  5011.8 1886.99  5012.3 1886.49  5021.9 1886.49  5022.4 1886.99
  5031.7 1887.73  5048.0 1894.24  5053.3 1893.15  5063.5 1895.28  5084.7 1896.61
  5109.7 1897.50  5135.3 1899.28  5190.8 1900.71  5233.3 1903.69  5270.1 1905.18
#Mann=3,-1,0
  4582.1    0.05       0  5011.8    0.05       0  5022.4    0.05       0
Bank Sta=5011.8,5022.4
Exp/Cntr=0.3,0.1

Chan Stop Cuts=-1