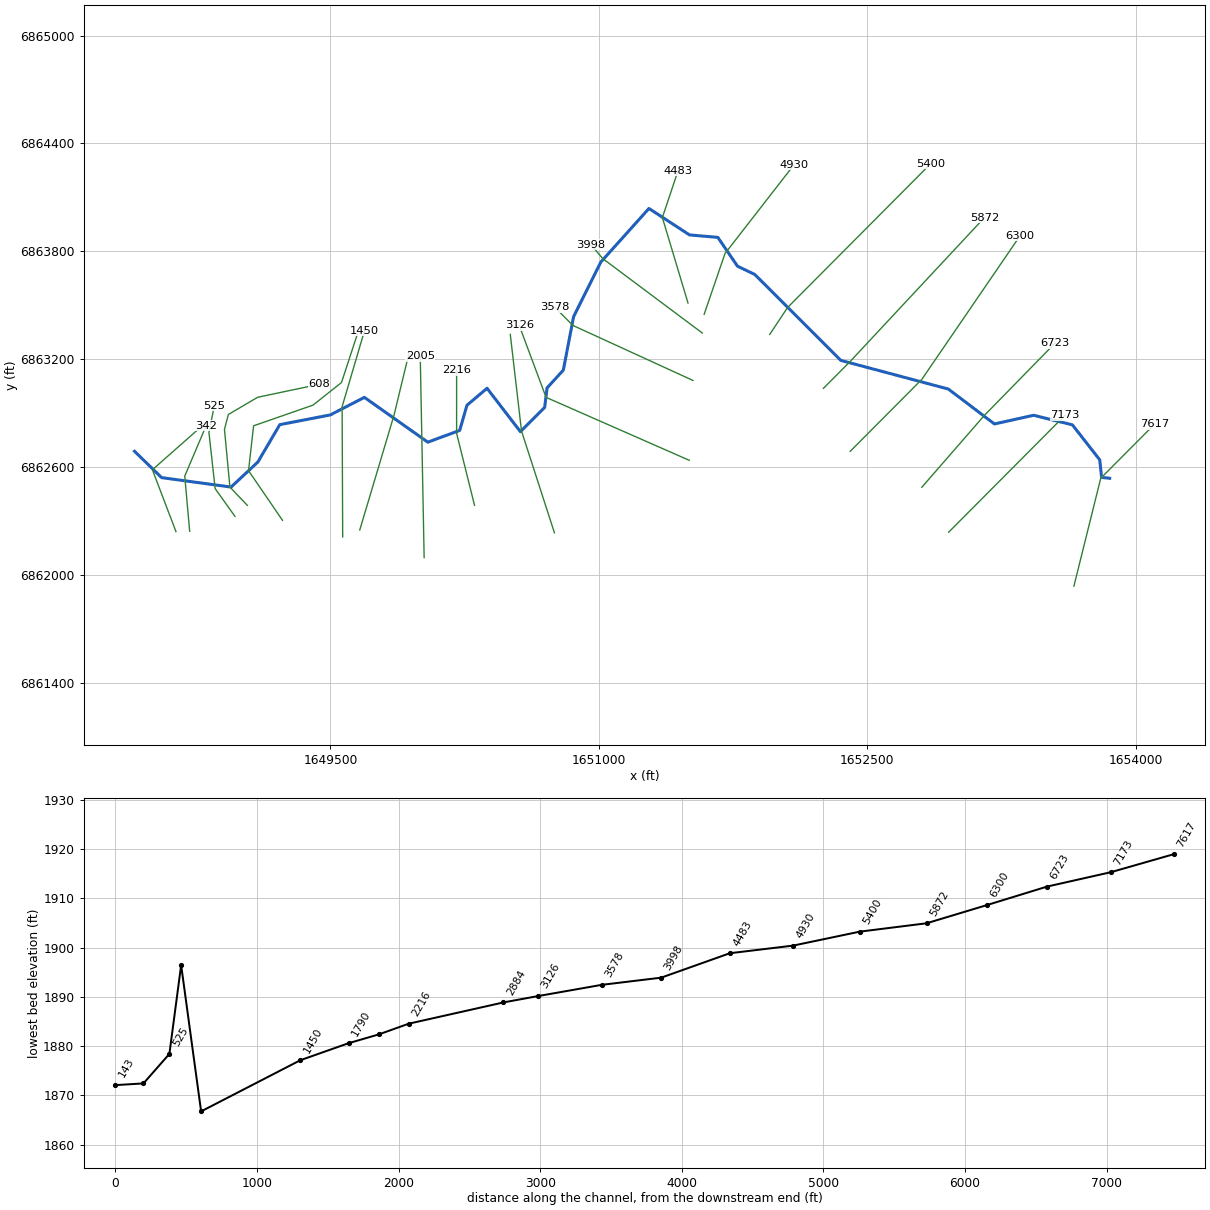
--- Deadman 63.prj (project) ---

Proj Title=Deadman 63 Base Level Engineering
Current Plan=p01
Default Exp/Contr=0.3,0.1
English Units
Geom File=g01
Flow File=f01
Plan File=p01
BEGIN DESCRIPTION:
Deadman 63
END DESCRIPTION:

--- Deadman 63.p01 (plan) ---

Plan Title=Multiple Run
Short Identifier=Multiple
Geom File=g01
Flow File=f01
Subcritical Flow
K Sum by GR= 0
Std Step Tol= 0.01
Critical Tol= 0.01
Num of Std Step Trials= 20
Max Error Tol= 0.3
Flow Tol Ratio= 0.001
Split Flow NTrial= 30
Split Flow Tol= 0.02
Split Flow Ratio= 0.02
Log Output Level= 0
Friction Slope Method= 1
Unsteady Friction Slope Method= 2
Unsteady Bridges Friction Slope Method= 1
Parabolic Critical Depth
Global Vel Dist=  1 , 1 , 1
Global Log Level= 0
CheckData=True
Encroach Param= -1, 0, 0, 0
BEGIN DESCRIPTION:
Multiple Run
END DESCRIPTION:

--- Deadman 63.f01 (steady flow) ---

Flow Title=Multiple
Number of Profiles=7
Profile Names=10-year,25-year,50-year,1pct_min,100-year,1pct_plu,500-year
River Rch & RM= Deadman 63,Reach-1,7617
     377     534     667     415     827    1650    1288
River Rch & RM= Deadman 63,Reach-1,2884
     378     535     667     414     825    1647    1281
Boundary for River Rch & Prof#=Deadman 63,Reach-1,1
Up Type=0
Dn Type=3
Dn Slope=0.009
Boundary for River Rch & Prof#=Deadman 63,Reach-1,2
Up Type=0
Dn Type=3
Dn Slope=0.009
Boundary for River Rch & Prof#=Deadman 63,Reach-1,3
Up Type=0
Dn Type=3
Dn Slope=0.009
Boundary for River Rch & Prof#=Deadman 63,Reach-1,4
Up Type=0
Dn Type=3
Dn Slope=0.009
Boundary for River Rch & Prof#=Deadman 63,Reach-1,5
Up Type=0
Dn Type=3
Dn Slope=0.009
Boundary for River Rch & Prof#=Deadman 63,Reach-1,6
Up Type=0
Dn Type=3
Dn Slope=0.009
Boundary for River Rch & Prof#=Deadman 63,Reach-1,7
Up Type=0
Dn Type=3
Dn Slope=0.009

--- Deadman 63.g01 (geometry) ---

Geom Title=Existing Conditions

River Reach=Deadman 63,Reach-1
Reach XY= 30
      1653855.00      6862538.00      1653809.75      6862542.68
      1653799.51      6862640.40      1653646.70      6862834.92
      1653430.00      6862888.40      1653210.86      6862840.05
      1652953.42      6863034.18      1652352.55      6863193.47
      1651871.67      6863671.35      1651774.77      6863717.58
      1651665.12      6863877.65      1651506.47      6863891.55
      1651279.96      6864038.51      1651010.85      6863740.29
      1650858.83      6863436.42      1650801.44      6863139.47
      1650710.54      6863040.42      1650697.14      6862931.83
      1650561.66      6862796.95      1650375.23      6863038.51
      1650262.86      6862944.19      1650222.21      6862804.27
      1650044.29      6862738.72      1649689.61      6862987.93
      1649499.07      6862890.25      1649216.87      6862836.26
      1649094.22      6862628.32      1648944.56      6862489.04
      1648556.46      6862541.53      1648405.00      6862688.00

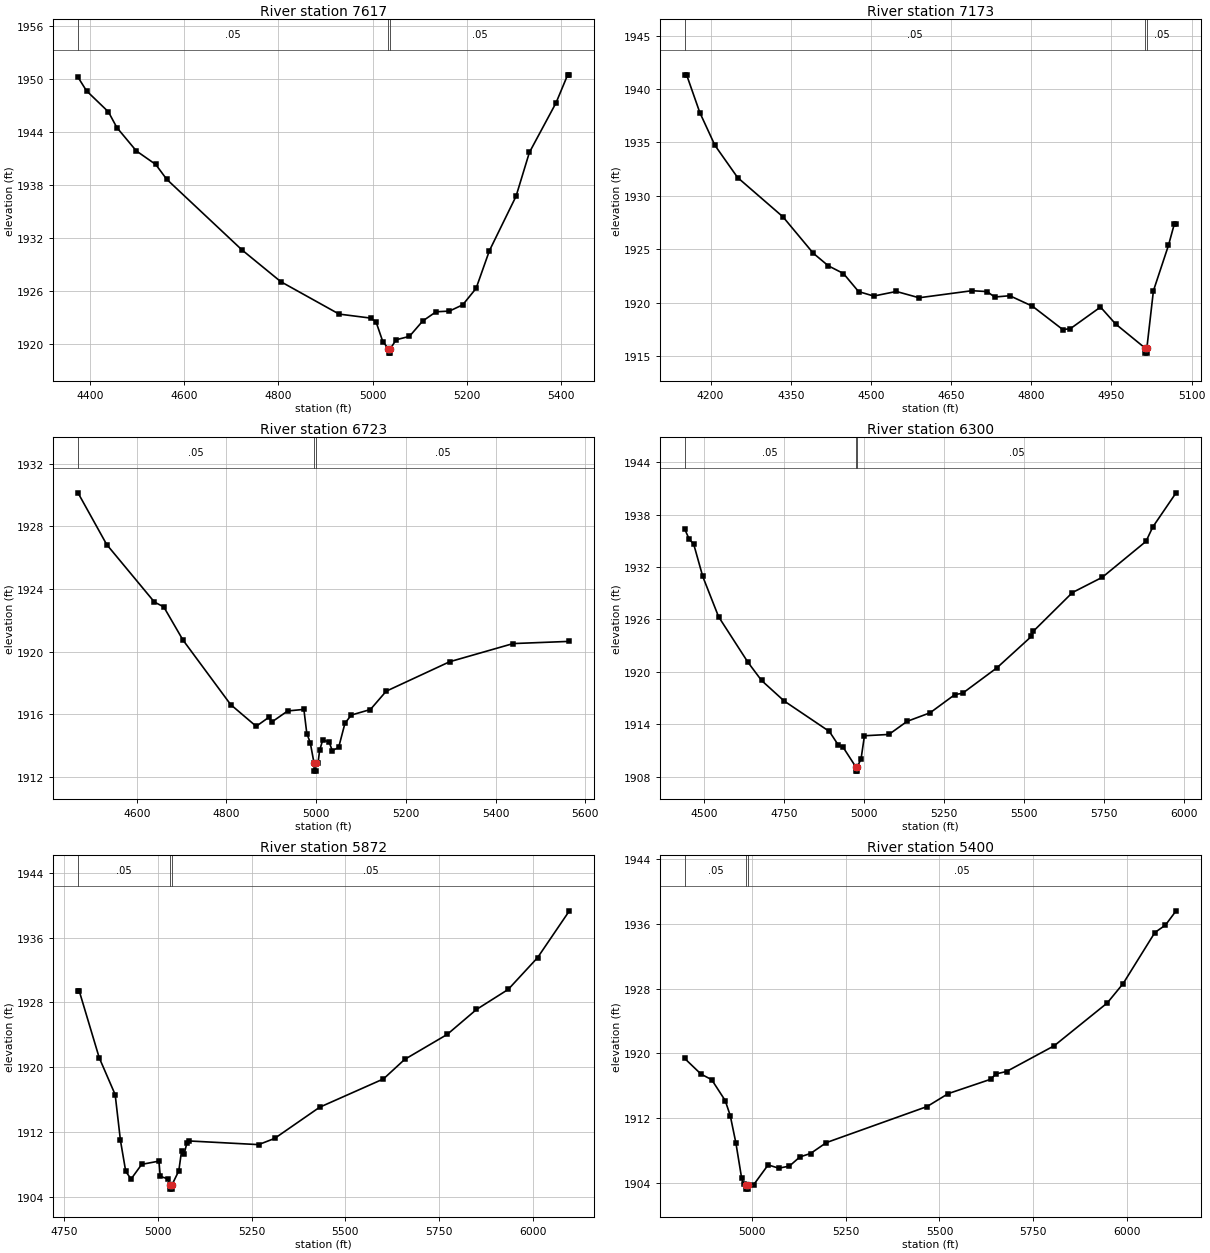
Type RM Length L Ch R = 1,7617,444,444,444
BEGIN DESCRIPTION:
Deadman 63 16.0
END DESCRIPTION:
XS GIS Cut Line= 3
      1653654.99      6861937.96      1653805.00      6862538.00
      1654105.02      6862838.02
#Sta/Elev= 30
  4374.8 1950.18  4392.9 1948.64  4439.3 1946.26  4457.3 1944.48  4498.5 1941.84
  4539.8 1940.30  4563.0 1938.63  4722.7 1930.63  4805.2 1927.03  4928.9 1923.36
  4996.8 1922.90  5007.5 1922.45  5021.6 1920.25  5033.7 1919.44  5034.0 1918.94
  5037.5 1918.94  5037.7 1919.44  5049.9 1920.45  5078.2 1920.84  5106.4 1922.58
  5134.7 1923.62  5163.0 1923.70  5191.3 1924.41  5219.6 1926.27  5247.9 1930.54
  5304.4 1936.70  5332.7 1941.66  5389.3 1947.28  5414.0 1950.45  5417.6 1950.45
#Mann=3,-1,0
  4374.8    0.05       0  5033.7    0.03       0  5037.7    0.05       0
Bank Sta=5033.7,5037.7
Exp/Cntr=0.3,0.1

Type RM Length L Ch R = 1,7173,450,450,450
BEGIN DESCRIPTION:
Deadman 63 15.0
END DESCRIPTION:
XS GIS Cut Line= 3
      1652954.97      6862237.97      1653555.00      6862838.00
      1653605.01      6862888.01
#Sta/Elev= 30
  4151.6 1941.33  4155.2 1941.33  4179.9 1937.80  4208.2 1934.73  4250.6 1931.72
  4335.5 1928.04  4392.1 1924.64  4420.3 1923.46  4448.6 1922.74  4476.9 1921.05
  4505.2 1920.63  4547.6 1921.06  4590.1 1920.47  4689.0 1921.13  4717.3 1921.05
  4731.5 1920.54  4759.8 1920.66  4802.2 1919.68  4858.8 1917.50  4872.9 1917.57
  4929.5 1919.60  4957.7 1918.02  5012.3 1915.79  5012.6 1915.29  5016.1 1915.29
  5016.3 1915.79  5028.5 1921.12  5056.7 1925.38  5067.4 1927.34  5070.9 1927.34
#Mann=3,-1,0
  4151.6    0.05       0  5012.3    0.05       0  5016.3    0.05       0
Bank Sta=5012.3,5016.3
Exp/Cntr=0.3,0.1

Type RM Length L Ch R = 1,6723,423,423,423
BEGIN DESCRIPTION:
Deadman 63 14.0
END DESCRIPTION:
XS GIS Cut Line= 3
      1652805.01      6862488.01      1653155.00      6862888.00
      1653550.22      6863290.10
#Sta/Elev= 30
  4469.0 1930.13  4533.0 1926.83  4639.3 1923.16  4660.2 1922.85  4702.9 1920.74
  4809.2 1916.62  4866.2 1915.23  4894.2 1915.80  4901.3 1915.51  4936.4 1916.21
  4972.5 1916.31  4979.1 1914.76  4986.7 1914.19  4995.2 1912.87  4995.4 1912.37
  4998.9 1912.37  4999.2 1912.87  5004.0 1912.87  5007.6 1913.70  5014.6 1914.36
  5028.7 1914.23  5035.8 1913.68  5050.0 1913.88  5064.1 1915.43  5078.3 1915.95
  5120.7 1916.30  5156.0 1917.47  5297.4 1919.35  5438.9 1920.51  5564.3 1920.65
#Mann=3,-1,0
  4469.0    0.05       0  4995.2    0.03       0  4999.2    0.05       0
Bank Sta=4995.2,4999.2
Exp/Cntr=0.3,0.1

Type RM Length L Ch R = 1,6300,428,428,428
BEGIN DESCRIPTION:
Deadman 63 13.0
END DESCRIPTION:
XS GIS Cut Line= 3
      1652405.03      6862688.03      1652805.00      6863088.00
      1653355.02      6863888.03
#Sta/Elev= 30
  4439.5 1936.36  4453.6 1935.19  4467.7 1934.62  4496.0 1930.92  4545.5 1926.31
  4637.4 1921.09  4679.9 1919.01  4750.6 1916.66  4892.0 1913.17  4920.3 1911.59
  4934.4 1911.39  4974.3 1909.13  4974.7 1908.63  4979.0 1908.63  4979.4 1909.13
  4991.0 1910.04  5001.6 1912.68  5078.0 1912.83  5135.0 1914.33  5206.8 1915.31
  5284.5 1917.40  5308.2 1917.54  5415.8 1920.46  5523.4 1924.05  5529.4 1924.64
  5651.9 1929.08  5745.4 1930.83  5881.9 1934.94  5903.2 1936.59  5976.0 1940.50
#Mann=3,-1,0
  4439.5    0.05       0  4974.3    0.03       0  4979.4    0.05       0
Bank Sta=4974.3,4979.4
Exp/Cntr=0.3,0.1

Type RM Length L Ch R = 1,5872,472,472,472
BEGIN DESCRIPTION:
Deadman 63 12.0
END DESCRIPTION:
XS GIS Cut Line= 3
      1652255.03      6863038.03      1652405.00      6863188.00
      1653155.02      6863988.02
#Sta/Elev= 30
  4787.8 1929.38  4791.3 1929.38  4844.3 1921.16  4886.8 1916.60  4900.9 1910.93
  4915.0 1907.10  4929.2 1906.17  4957.5 1907.98  5003.3 1908.38  5007.0 1906.50
  5028.0 1906.17  5032.7 1905.42  5033.1 1904.92  5037.4 1904.92  5037.8 1905.42
  5056.3 1907.18  5063.6 1909.62  5070.5 1909.27  5077.8 1910.60  5084.6 1910.87
  5268.8 1910.42  5311.3 1911.18  5431.4 1915.04  5601.4 1918.54  5657.8 1920.95
  5770.9 1924.03  5849.1 1927.12  5933.6 1929.60  6011.7 1933.52  6096.5 1939.31
#Mann=3,-1,0
  4787.8    0.05       0  5032.7    0.03       0  5037.8    0.05       0
Bank Sta=5032.7,5037.8
Exp/Cntr=0.3,0.1

Type RM Length L Ch R = 1,5400,470,470,470
BEGIN DESCRIPTION:
Deadman 63 11.0
END DESCRIPTION:
XS GIS Cut Line= 3
      1651954.99      6863337.99      1652055.00      6863488.00
      1652855.02      6864288.02
#Sta/Elev= 30
  4819.9 1919.36  4863.5 1917.43  4892.0 1916.74  4928.1 1914.16  4941.6 1912.29
  4956.6 1908.92  4971.7 1904.64  4977.7 1903.81  4984.1 1903.72  4984.5 1903.22
  4988.9 1903.22  4989.2 1903.72  5003.7 1903.74  5042.6 1906.21  5070.9 1905.81
  5099.2 1906.06  5127.5 1907.20  5155.8 1907.62  5198.2 1908.97  5466.9 1913.42
  5523.5 1915.02  5636.6 1916.79  5650.7 1917.45  5679.0 1917.75  5806.3 1920.93
  5947.7 1926.21  5990.1 1928.60  6075.0 1934.92  6103.3 1935.84  6131.6 1937.60
#Mann=3,-1,0
  4819.9    0.05       0  4984.1    0.03       0  4989.2    0.05       0
Bank Sta=4984.1,4989.2
Exp/Cntr=0.3,0.1

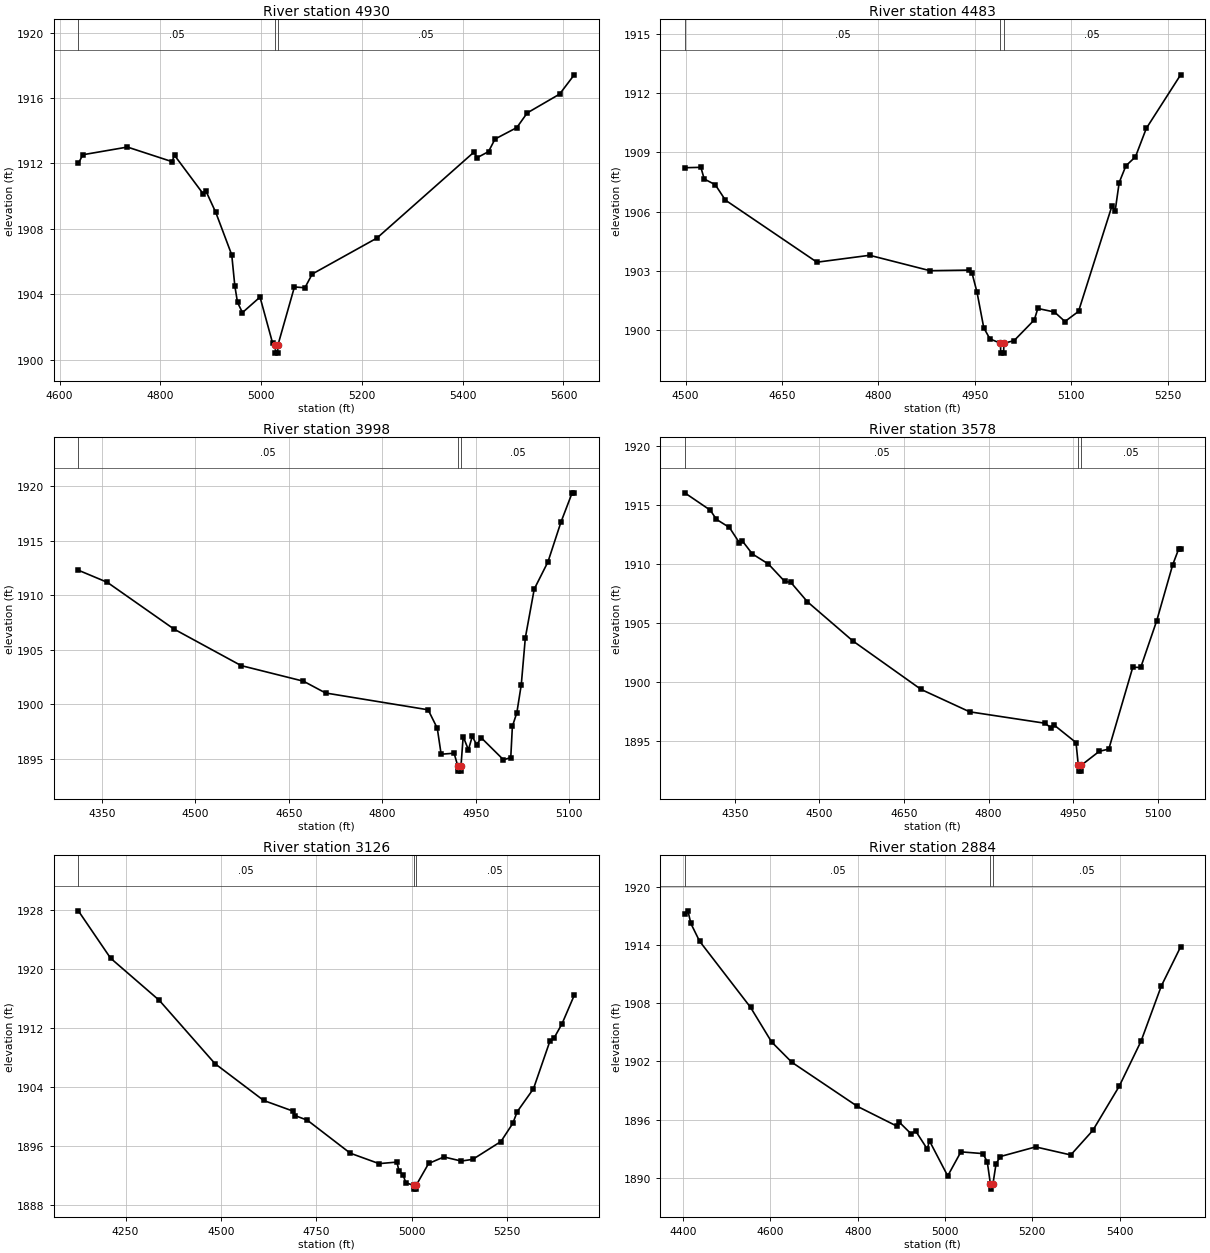
Type RM Length L Ch R = 1,4930,447,447,447
BEGIN DESCRIPTION:
Deadman 63 10.0
END DESCRIPTION:
XS GIS Cut Line= 3
      1651588.60      6863450.05      1651705.00      6863788.00
      1652090.91      6864281.87
#Sta/Elev= 30
  4637.1 1912.00  4646.1 1912.53  4734.5 1913.00  4822.8 1912.11  4828.1 1912.49
  4885.3 1910.12  4890.6 1910.29  4909.9 1909.00  4941.6 1906.40  4947.7 1904.50
  4953.0 1903.50  4962.8 1902.87  4997.7 1903.82  5022.6 1901.01  5028.0 1900.89
  5028.4 1900.39  5032.9 1900.39  5033.3 1900.89  5066.0 1904.44  5086.8 1904.39
  5101.3 1905.23  5229.7 1907.43  5422.3 1912.69  5428.6 1912.35  5451.2 1912.72
  5464.1 1913.49  5507.3 1914.19  5528.1 1915.09  5592.3 1916.24  5621.3 1917.42
#Mann=3,-1,0
  4637.1    0.05       0  5028.0    0.03       0  5033.3    0.05       0
Bank Sta=5028,5033.3
Exp/Cntr=0.3,0.1

Type RM Length L Ch R = 1,4483,485,485,485
BEGIN DESCRIPTION:
Deadman 63 9.0
END DESCRIPTION:
XS GIS Cut Line= 3
      1651498.31      6863512.52      1651355.00      6863988.00
      1651442.75      6864248.61
#Sta/Elev= 30
  4498.7 1908.22  4523.8 1908.24  4529.0 1907.65  4546.2 1907.36  4562.0 1906.58
  4704.4 1903.44  4786.4 1903.79  4880.4 1903.01  4940.6 1903.04  4945.8 1902.88
  4953.5 1901.92  4964.0 1900.12  4973.6 1899.56  4990.0 1899.34  4990.4 1898.84
  4994.9 1898.84  4995.3 1899.34  5011.1 1899.47  5042.6 1900.52  5048.1 1901.10
  5074.0 1900.92  5090.3 1900.44  5111.4 1900.95  5163.3 1906.27  5168.5 1906.05
  5174.7 1907.47  5185.2 1908.32  5200.0 1908.77  5216.9 1910.21  5270.3 1912.92
#Mann=3,-1,0
  4498.7    0.05       0  4990.0    0.05       0  4995.3    0.05       0
Bank Sta=4990,4995.3
Exp/Cntr=0.3,0.1

Type RM Length L Ch R = 1,3998,420,420,420
BEGIN DESCRIPTION:
Deadman 63 8.0
END DESCRIPTION:
XS GIS Cut Line= 3
      1651578.17      6863345.84      1651022.62      6863759.03
      1650955.02      6863837.98
#Sta/Elev= 30
  4311.9 1912.29  4358.4 1911.18  4465.4 1906.90  4573.3 1903.55  4673.4 1902.12
  4708.9 1901.04  4873.6 1899.50  4888.3 1897.81  4894.5 1895.43  4915.3 1895.52
  4921.1 1894.38  4921.5 1893.88  4926.0 1893.88  4926.4 1894.38  4929.9 1897.05
  4938.3 1895.83  4944.5 1897.07  4951.4 1896.31  4959.2 1896.92  4994.6 1894.92
  5006.3 1895.12  5008.9 1897.98  5016.1 1899.24  5023.2 1901.81  5029.7 1906.10
  5044.0 1910.56  5066.0 1913.05  5086.8 1916.68  5104.9 1919.38  5108.2 1919.38
#Mann=3,-1,0
  4311.9    0.05       0  4921.1    0.03       0  4926.4    0.05       0
Bank Sta=4921.1,4926.4
Exp/Cntr=0.3,0.1

Type RM Length L Ch R = 1,3578,452,452,452
BEGIN DESCRIPTION:
Deadman 63 7.0
END DESCRIPTION:
XS GIS Cut Line= 3
      1651526.09      6863081.95      1650855.00      6863388.00
      1650755.00      6863488.00
#Sta/Elev= 30
  4261.3 1916.02  4306.5 1914.55  4317.5 1913.77  4340.5 1913.08  4358.1 1911.79
  4363.6 1911.93  4381.1 1910.84  4409.7 1909.98  4438.4 1908.51  4449.3 1908.43
  4478.8 1906.78  4559.3 1903.46  4680.2 1899.35  4766.3 1897.45  4900.0 1896.48
  4910.0 1896.11  4915.5 1896.35  4954.9 1894.84  4958.9 1892.92  4959.3 1892.42
  4963.8 1892.42  4964.3 1892.92  4996.1 1894.10  5013.0 1894.29  5055.5 1901.23
  5069.6 1901.21  5097.9 1905.17  5126.2 1909.91  5136.8 1911.25  5140.3 1911.25
#Mann=3,-1,0
  4261.3    0.05       0  4958.9    0.03       0  4964.3    0.05       0
Bank Sta=4958.9,4964.3
Exp/Cntr=0.3,0.1

Type RM Length L Ch R = 1,3126,242,242,242
BEGIN DESCRIPTION:
Deadman 63 6.0
END DESCRIPTION:
XS GIS Cut Line= 3
      1651505.02      6862637.99      1650705.00      6862988.00
      1650555.01      6863387.97
#Sta/Elev= 30
  4126.3 1927.90  4210.9 1921.47  4338.8 1915.74  4484.6 1907.16  4612.4 1902.16
  4688.1 1900.74  4693.9 1900.12  4726.7 1899.49  4839.3 1895.01  4914.9 1893.59
  4961.7 1893.80  4967.2 1892.59  4977.7 1892.09  4985.1 1890.99  5006.6 1890.63
  5007.0 1890.13  5011.6 1890.13  5012.0 1890.63  5044.9 1893.61  5085.0 1894.50
  5130.4 1893.94  5160.6 1894.17  5234.5 1896.59  5265.6 1899.05  5277.2 1900.64
  5319.9 1903.76  5362.7 1910.18  5373.3 1910.59  5394.7 1912.57  5426.7 1916.43
#Mann=3,-1,0
  4126.3    0.05       0  5006.6    0.03       0  5012.0    0.05       0
Bank Sta=5006.6,5012
Exp/Cntr=0.3,0.1

Type RM Length L Ch R = 1,2884,668,668,668
BEGIN DESCRIPTION:
Deadman 63 5.0
END DESCRIPTION:
XS GIS Cut Line= 3
      1650751.79      6862234.70      1650567.75      6862800.70
      1650505.00      6863337.98
#Sta/Elev= 30
  4403.6 1917.23  4410.9 1917.52  4417.6 1916.22  4437.5 1914.40  4554.3 1907.58
  4602.5 1904.02  4648.9 1901.92  4799.4 1897.37  4890.0 1895.33  4895.3 1895.74
  4921.9 1894.56  4932.8 1894.83  4959.1 1892.99  4964.4 1893.81  5006.1 1890.21
  5036.3 1892.69  5086.7 1892.51  5096.7 1891.67  5104.0 1889.35  5104.4 1888.85
  5109.6 1889.35  5116.9 1891.48  5126.9 1892.21  5207.5 1893.20  5288.0 1892.37
  5338.4 1894.89  5398.8 1899.43  5449.1 1904.10  5495.5 1909.78  5539.7 1913.81
#Mann=3,-1,0
  4403.6    0.05       0  5104.0    0.03       0  5109.6    0.05       0
Bank Sta=5104,5109.6
Exp/Cntr=0.3,0.1

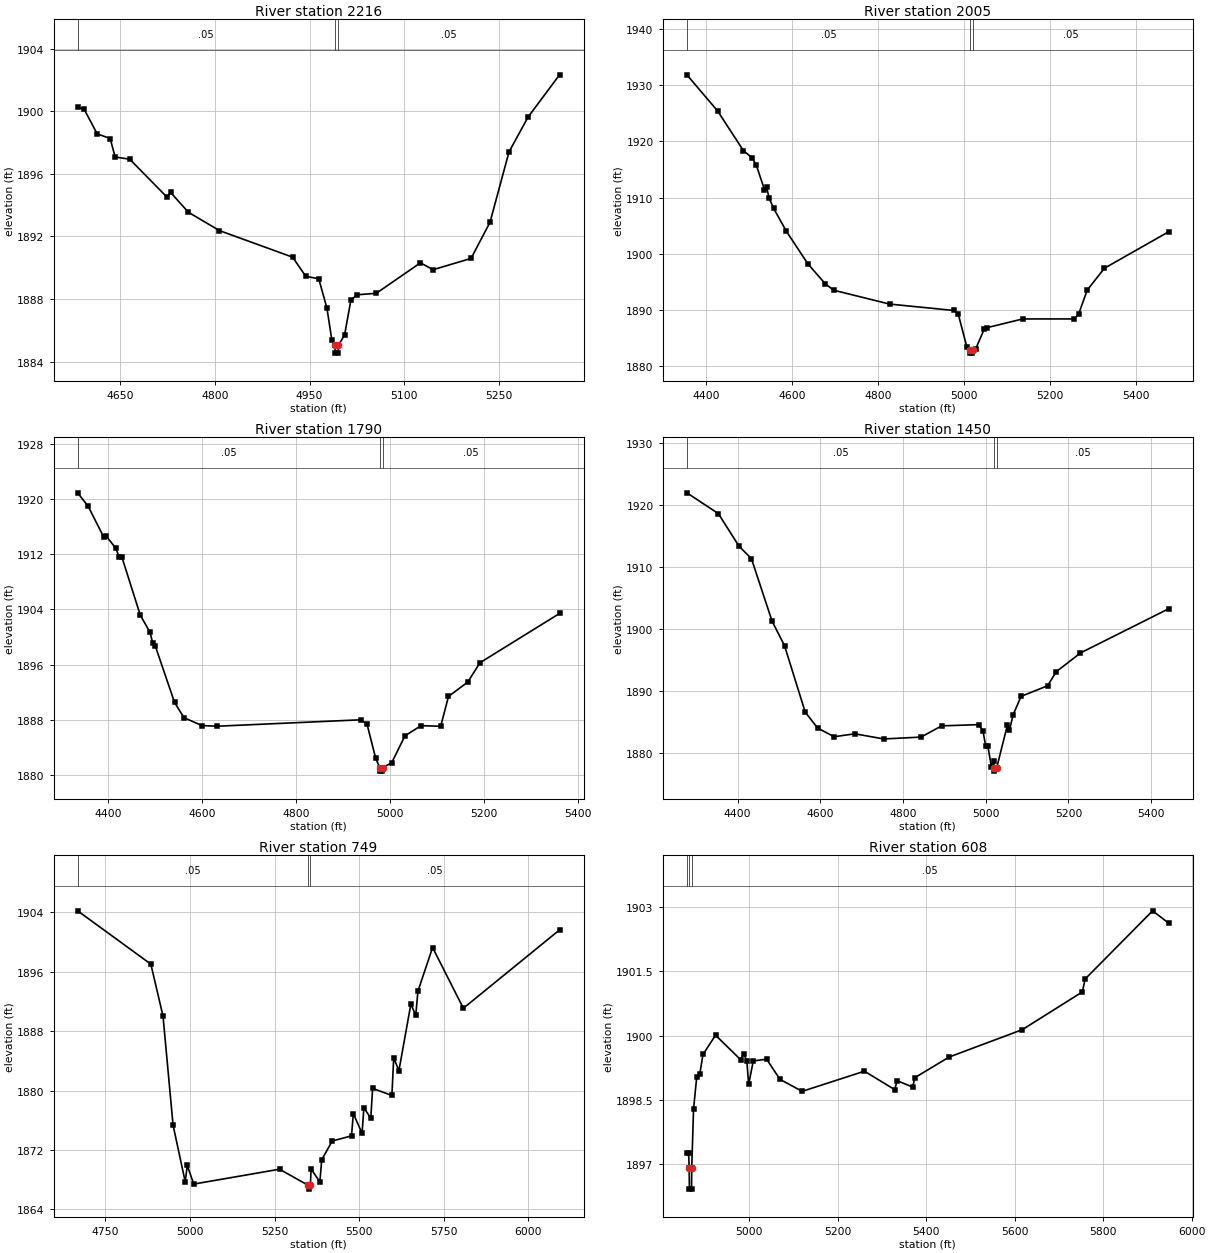
Type RM Length L Ch R = 1,2216,211,211,211
BEGIN DESCRIPTION:
Deadman 63 4.0
END DESCRIPTION:
XS GIS Cut Line= 3
      1650305.00      6862388.02      1650205.00      6862788.00
      1650205.00      6863138.01
#Sta/Elev= 30
  4583.2 1900.25  4593.5 1900.12  4614.1 1898.55  4634.7 1898.25  4642.5 1897.07
  4665.6 1896.93  4724.9 1894.49  4730.1 1894.81  4758.4 1893.54  4807.4 1892.37
  4923.3 1890.67  4944.0 1889.45  4964.6 1889.29  4977.5 1887.42  4985.2 1885.41
  4990.1 1885.04  4990.6 1884.54  4995.3 1884.54  4995.8 1885.04  5005.5 1885.71
  5015.5 1887.94  5025.5 1888.27  5055.5 1888.36  5125.5 1890.31  5145.5 1889.87
  5205.5 1890.59  5235.5 1892.90  5265.5 1897.39  5295.5 1899.61  5345.5 1902.32
#Mann=3,-1,0
  4583.2    0.05       0  4990.1    0.05       0  4995.8    0.05       0
Bank Sta=4990.1,4995.8
Exp/Cntr=0.3,0.1

Type RM Length L Ch R = 1,2005,215,215,215
BEGIN DESCRIPTION:
Mapping XS 42b75167
END DESCRIPTION:
XS GIS Cut Line= 2
      1650023.58      6862096.46      1650001.82      6863217.75
#Sta/Elev= 30
  4355.6 1931.78  4427.2 1925.36  4487.2 1918.32  4507.2 1917.06  4517.2 1915.73
  4536.1 1911.42  4541.1 1911.83  4547.2 1909.84  4557.2 1908.13  4587.2 1904.00
  4637.2 1898.22  4677.2 1894.72  4697.2 1893.54  4827.2 1891.08  4977.3 1889.94
  4987.3 1889.26  5007.3 1883.40  5014.8 1882.87  5015.3 1882.37  5020.1 1882.37
  5020.5 1882.87  5027.3 1883.05  5047.3 1886.57  5053.9 1886.89  5137.3 1888.44
  5257.3 1888.44  5267.3 1889.31  5287.3 1893.56  5327.3 1897.44  5477.1 1903.93
#Mann=3,-1,0
  4355.6    0.05       0  5014.8    0.03       0  5020.5    0.05       0
Bank Sta=5014.8,5020.5
Exp/Cntr=0.3,0.1

Type RM Length L Ch R = 1,1790,340,340,340
BEGIN DESCRIPTION:
Deadman 63 3.0
END DESCRIPTION:
XS GIS Cut Line= 3
      1649663.79      6862250.48      1649855.00      6862888.00
      1649939.89      6863237.76
#Sta/Elev= 30
  4335.6 1920.90  4358.2 1918.92  4391.2 1914.48  4396.5 1914.62  4416.5 1912.89
  4424.3 1911.56  4429.5 1911.65  4468.7 1903.21  4489.6 1900.67  4495.6 1899.08
  4500.9 1898.69  4541.8 1890.53  4561.8 1888.32  4600.1 1887.17  4633.1 1887.08
  4938.5 1888.01  4951.6 1887.33  4969.9 1882.41  4978.7 1881.07  4979.1 1880.57
  4983.9 1880.57  4984.4 1881.07  5003.8 1881.77  5032.1 1885.68  5066.4 1887.16
  5108.2 1887.07  5124.7 1891.39  5165.8 1893.48  5191.8 1896.28  5361.1 1903.42
#Mann=3,-1,0
  4335.6    0.05       0  4978.7    0.05       0  4984.4    0.05       0
Bank Sta=4978.7,4984.4
Exp/Cntr=0.3,0.1

Type RM Length L Ch R = 1,1450,701,701,701
BEGIN DESCRIPTION:
Deadman 63 2.0
END DESCRIPTION:
XS GIS Cut Line= 3
      1649568.39      6862211.92      1649565.15      6862936.12
      1649690.26      6863358.99
#Sta/Elev= 30
  4277.5 1922.01  4353.6 1918.66  4403.6 1913.40  4433.6 1911.39  4483.6 1901.29
  4513.6 1897.36  4563.6 1886.64  4593.6 1884.07  4633.6 1882.67  4683.6 1883.14
  4753.6 1882.31  4843.6 1882.61  4893.6 1884.42  4983.6 1884.62  4993.6 1883.53
  5000.1 1881.13  5005.3 1881.13  5013.8 1877.84  5019.1 1878.82  5020.8 1877.62
  5021.2 1877.12  5026.5 1877.62  5052.3 1884.50  5057.5 1883.71  5066.2 1886.19
  5085.6 1889.18  5149.7 1890.89  5170.5 1893.15  5229.1 1896.18  5442.7 1903.32
#Mann=3,-1,0
  4277.5    0.05       0  5020.8    0.05       0  5026.5    0.05       0
Bank Sta=5020.8,5026.5
Exp/Cntr=0.3,0.1

Type RM Length L Ch R = 1,749,141,141,141
BEGIN DESCRIPTION:
Mapping XS c0333c21
END DESCRIPTION:
XS GIS Cut Line= 6
      1649232.02      6862304.00      1649042.15      6862580.21
      1649070.36      6862829.78      1649402.39      6862944.80
      1649561.70      6863070.46      1649650.21      6863339.34
#Sta/Elev= 30
  4668.1 1904.21  4884.4 1897.03  4920.3 1890.04  4950.0 1875.35  4985.9 1867.72
  4992.0 1869.92  5011.1 1867.41  5264.5 1869.41  5349.7 1867.23  5350.2 1866.73
  5355.5 1867.23  5357.9 1869.43  5383.8 1867.71  5389.1 1870.67  5420.2 1873.21
  5477.2 1873.90  5482.5 1876.90  5508.4 1874.24  5513.7 1877.69  5534.2 1876.27
  5539.5 1880.30  5596.5 1879.34  5601.8 1884.39  5617.3 1882.69  5652.5 1891.65
  5667.0 1890.14  5673.4 1893.38  5716.7 1899.27  5807.6 1891.09  6091.8 1901.64
#Mann=3,-1,0
  4668.1    0.05       0  5349.7    0.05       0  5355.5    0.05       0
Bank Sta=5349.7,5355.5
Exp/Cntr=0.3,0.1

Type RM Length L Ch R = 1,608,83,83,83
BEGIN DESCRIPTION:
Mapping XS 2a6203f0
END DESCRIPTION:
XS GIS Cut Line= 6
      1649035.61      6862387.10      1648937.98      6862489.07
      1648907.60      6862810.25      1648929.30      6862892.71
      1649093.12      6862988.46      1649436.14      6863060.41
#Sta/Elev= 30
  4859.0 1897.26  4863.0 1897.26  4864.2 1896.92  4864.7 1896.42  4869.5 1896.42
  4870.0 1896.92  4874.1 1898.29  4881.3 1899.04  4888.2 1899.10  4895.4 1899.56
  4923.8 1900.01  4980.4 1899.44  4987.3 1899.58  4994.5 1899.41  4998.7 1898.86
  5009.1 1899.41  5039.3 1899.45  5069.4 1898.98  5119.6 1898.70  5260.3 1899.17
  5328.9 1898.74  5334.1 1898.95  5369.3 1898.80  5374.4 1899.02  5451.7 1899.50
  5617.4 1900.14  5753.0 1901.02  5759.2 1901.32  5911.7 1902.91  5948.3 1902.62
#Mann=3,-1,0
  4859.0    0.05       0  4864.2    0.05       0  4870.0    0.05       0
Bank Sta=4864.2,4870
Exp/Cntr=0.3,0.1

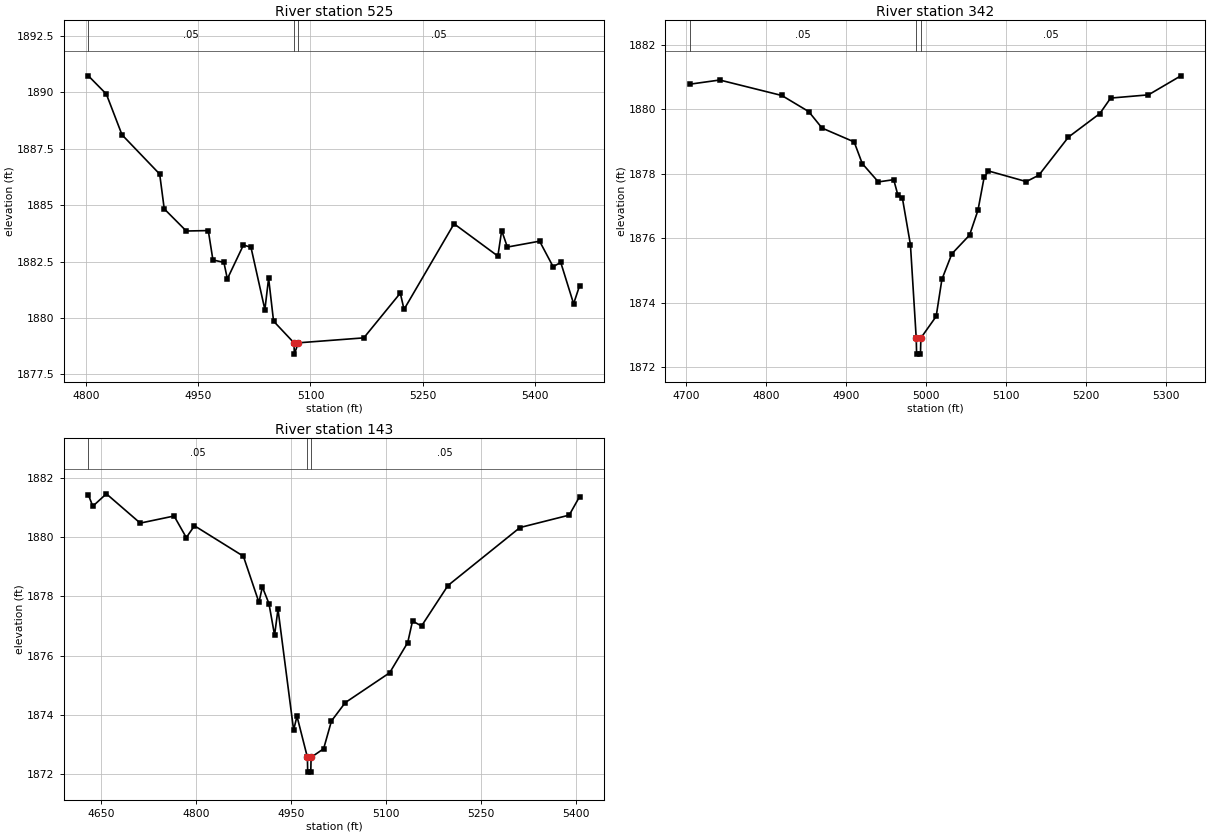
Type RM Length L Ch R = 1,525,183,183,183
BEGIN DESCRIPTION:
Mapping XS da881926
END DESCRIPTION:
XS GIS Cut Line= 4
      1648966.19      6862326.32      1648855.52      6862480.39
      1648820.79      6862792.89      1648851.17      6862942.61
#Sta/Elev= 30
  4802.9 1890.72  4827.0 1889.91  4847.9 1888.11  4898.3 1886.37  4904.4 1884.83
  4933.9 1883.85  4963.3 1883.87  4969.5 1882.57  4984.2 1882.46  4988.8 1881.73
  5010.3 1883.23  5020.4 1883.13  5039.0 1880.37  5044.0 1881.76  5050.6 1879.86
  5077.9 1878.90  5078.4 1878.40  5083.7 1878.90  5171.3 1879.12  5220.1 1881.10
  5225.1 1880.38  5292.0 1884.17  5350.6 1882.74  5355.7 1883.87  5363.3 1883.14
  5406.4 1883.40  5424.5 1882.27  5434.7 1882.46  5451.9 1880.63  5459.8 1881.42
#Mann=3,-1,0
  4802.9    0.05       0  5077.9    0.05       0  5083.7    0.05       0
Bank Sta=5077.9,5083.7
Exp/Cntr=0.3,0.1

Type RM Length L Ch R = 1,342,199,199,199
BEGIN DESCRIPTION:
Mapping XS 3f4b1b67
END DESCRIPTION:
XS GIS Cut Line= 3
      1648713.15      6862243.39      1648685.64      6862550.00
      1648805.53      6862831.06
#Sta/Elev= 30
  4704.7 1880.78  4742.2 1880.91  4819.8 1880.43  4853.4 1879.93  4870.0 1879.42
  4910.1 1878.99  4920.2 1878.32  4940.3 1877.75  4959.5 1877.82  4964.5 1877.36
  4970.4 1877.24  4980.4 1875.80  4987.6 1872.91  4988.1 1872.41  4992.9 1872.41
  4993.4 1872.91  5012.5 1873.58  5019.7 1874.73  5032.1 1875.52  5054.2 1876.10
  5064.7 1876.87  5072.4 1877.89  5077.8 1878.09  5125.1 1877.76  5140.8 1877.96
  5177.7 1879.14  5216.9 1879.87  5230.4 1880.35  5277.6 1880.45  5318.1 1881.04
#Mann=3,-1,0
  4704.7    0.05       0  4987.6    0.05       0  4993.4    0.05       0
Bank Sta=4987.6,4993.4
Exp/Cntr=0.3,0.1

Type RM Length L Ch R = 1,143,0,0,0
BEGIN DESCRIPTION:
Deadman 63 1.0
END DESCRIPTION:
XS GIS Cut Line= 3
      1648636.50      6862241.42      1648504.82      6862585.38
      1648811.33      6862854.51
#Sta/Elev= 30
  4630.1 1881.44  4637.1 1881.05  4658.6 1881.47  4712.1 1880.48  4765.6 1880.72
  4784.9 1879.99  4797.8 1880.39  4875.1 1879.36  4899.7 1877.80  4905.1 1878.32
  4915.5 1877.76  4924.4 1876.69  4929.8 1877.57  4954.5 1873.48  4959.8 1873.95
  4976.3 1872.56  4976.7 1872.06  4981.6 1872.06  4982.1 1872.56  5001.9 1872.85
  5014.3 1873.79  5036.1 1874.41  5106.3 1875.42  5134.8 1876.44  5142.4 1877.17
  5156.6 1877.00  5198.4 1878.37  5312.2 1880.33  5390.0 1880.75  5406.3 1881.37
#Mann=3,-1,0
  4630.1    0.05       0  4976.3    0.05       0  4982.1    0.05       0
Bank Sta=4976.3,4982.1
Exp/Cntr=0.3,0.1

Chan Stop Cuts=-1