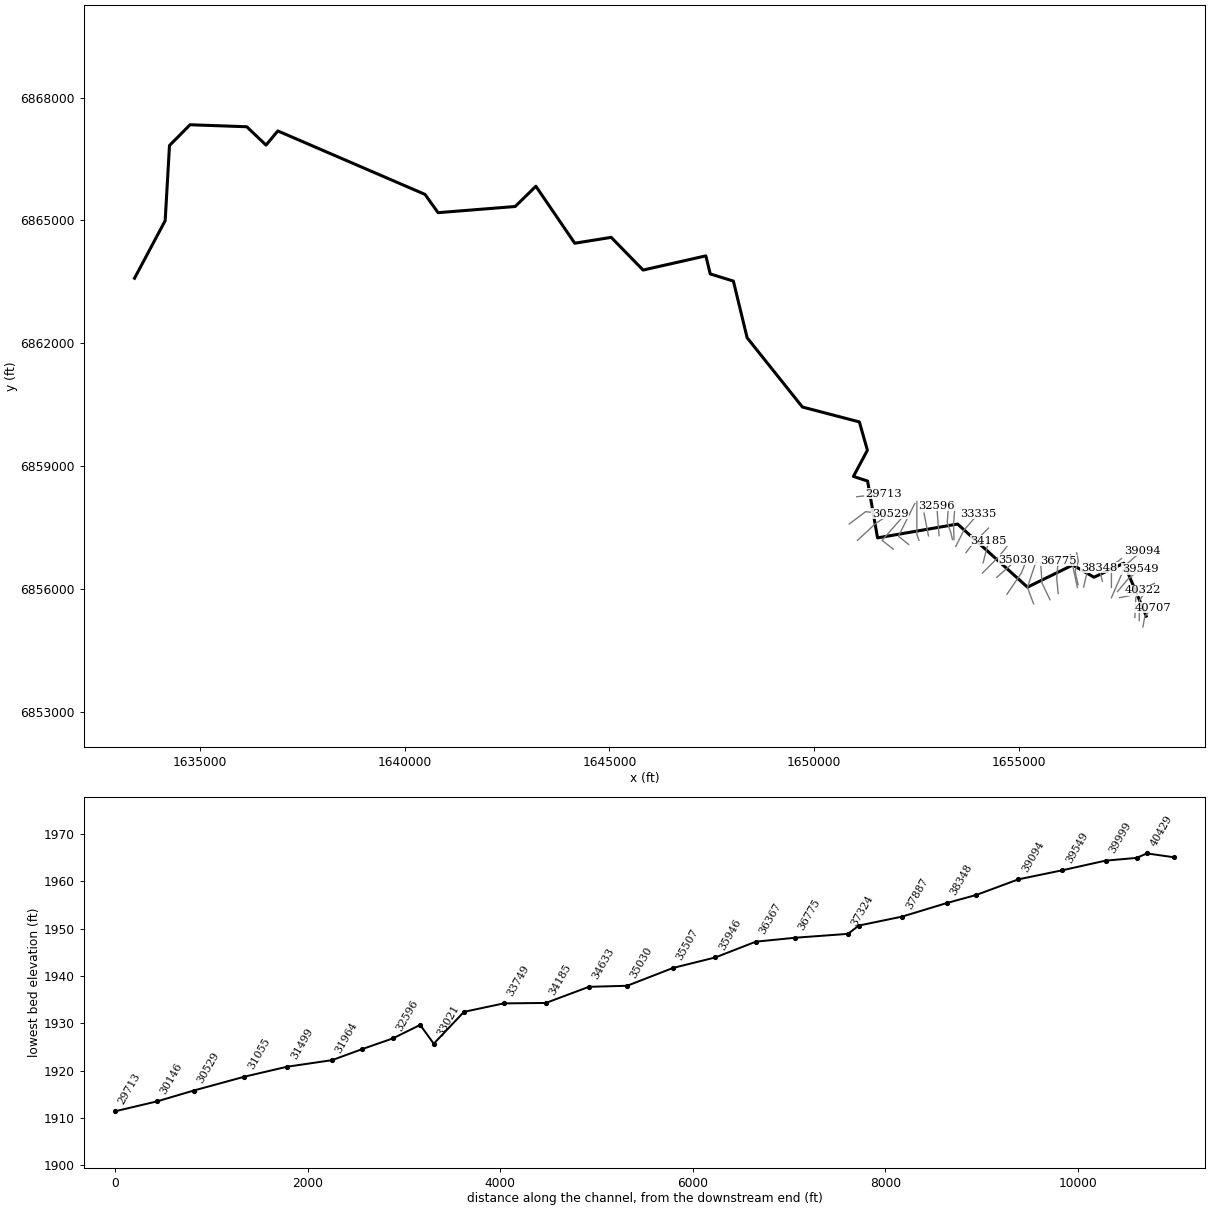
--- Deadman 64.prj (project) ---

Proj Title=Deadman 64 Base Level Engineering
Current Plan=p01
Default Exp/Contr=0.3,0.1
English Units
Geom File=g01
Flow File=f01
Plan File=p01
BEGIN DESCRIPTION:
Deadman 64
END DESCRIPTION:

--- Deadman 64.p01 (plan) ---

Plan Title=Multiple Run
Short Identifier=Multiple
Geom File=g01
Flow File=f01
Subcritical Flow
K Sum by GR= 0
Std Step Tol= 0.01
Critical Tol= 0.01
Num of Std Step Trials= 20
Max Error Tol= 0.3
Flow Tol Ratio= 0.001
Split Flow NTrial= 30
Split Flow Tol= 0.02
Split Flow Ratio= 0.02
Log Output Level= 0
Friction Slope Method= 1
Unsteady Friction Slope Method= 2
Unsteady Bridges Friction Slope Method= 1
Parabolic Critical Depth
Global Vel Dist=  1 , 1 , 1
Global Log Level= 0
CheckData=True
Encroach Param= -1, 0, 0, 0
BEGIN DESCRIPTION:
Multiple Run
END DESCRIPTION:

--- Deadman 64.f01 (steady flow) ---

Flow Title=Multiple
Number of Profiles=7
Profile Names=10-year,25-year,50-year,1pct_min,100-year,1pct_plu,500-year
River Rch & RM= Deadman 64,Reach-1,40707
     327     456     563     346     691    1378    1051
River Rch & RM= Deadman 64,Reach-1,34633
     353     494     612     377     752    1501    1152
River Rch & RM= Deadman 64,Reach-1,30529
     463     657     822     511    1019    2033    1588
River Rch & RM= Deadman 64,Reach-1,28825
     557     798    1004     627    1251    2496    1969
River Rch & RM= Deadman 64,Reach-1,22785
     832    1213    1544     975    1946    3883    3133
River Rch & RM= Deadman 64,Reach-1,20396
     892    1303    1661    1050    2094    4179    3377
River Rch & RM= Deadman 64,Reach-1,14206
     950    1391    1774    1122    2239    4468    3617
River Rch & RM= Deadman 64,Reach-1,10137
    1018    1493    1908    1208    2411    4811    3905
River Rch & RM= Deadman 64,Reach-1,3684
    1033    1515    1935    1226    2446    4880    3959
Boundary for River Rch & Prof#=Deadman 64,Reach-1,1
Up Type=0
Dn Type=3
Dn Slope=0.007
Boundary for River Rch & Prof#=Deadman 64,Reach-1,2
Up Type=0
Dn Type=3
Dn Slope=0.007
Boundary for River Rch & Prof#=Deadman 64,Reach-1,3
Up Type=0
Dn Type=3
Dn Slope=0.007
Boundary for River Rch & Prof#=Deadman 64,Reach-1,4
Up Type=0
Dn Type=3
Dn Slope=0.007
Boundary for River Rch & Prof#=Deadman 64,Reach-1,5
Up Type=0
Dn Type=3
Dn Slope=0.007
Boundary for River Rch & Prof#=Deadman 64,Reach-1,6
Up Type=0
Dn Type=3
Dn Slope=0.007
Boundary for River Rch & Prof#=Deadman 64,Reach-1,7
Up Type=0
Dn Type=3
Dn Slope=0.007

--- Deadman 64.g01 (geometry) ---

Geom Title=Existing Conditions

River Reach=Deadman 64,Reach-1
Reach XY= 30
      1658105.00      6855338.00      1657558.42      6856630.21
      1656830.22      6856287.67      1656310.72      6856586.10
      1655204.90      6856045.28      1653499.15      6857585.94
      1651545.29      6857248.75      1651301.57      6858636.78
      1650955.86      6858748.31      1651297.69      6859387.90
      1651101.65      6860079.91      1649710.59      6860443.61
      1648360.83      6862135.70      1648025.58      6863518.42
      1647460.18      6863693.41      1647353.78      6864134.57
      1645820.40      6863788.09      1645043.05      6864586.08
      1644152.55      6864443.46      1643203.54      6865834.48
      1642699.35      6865339.97      1640815.44      6865189.04
      1640497.05      6865634.99      1636903.23      6867184.70
      1636615.43      6866839.05      1636144.57      6867286.95
      1634760.85      6867335.94      1634258.49      6866829.52
      1634152.93      6864993.86      1633405.00      6863588.00

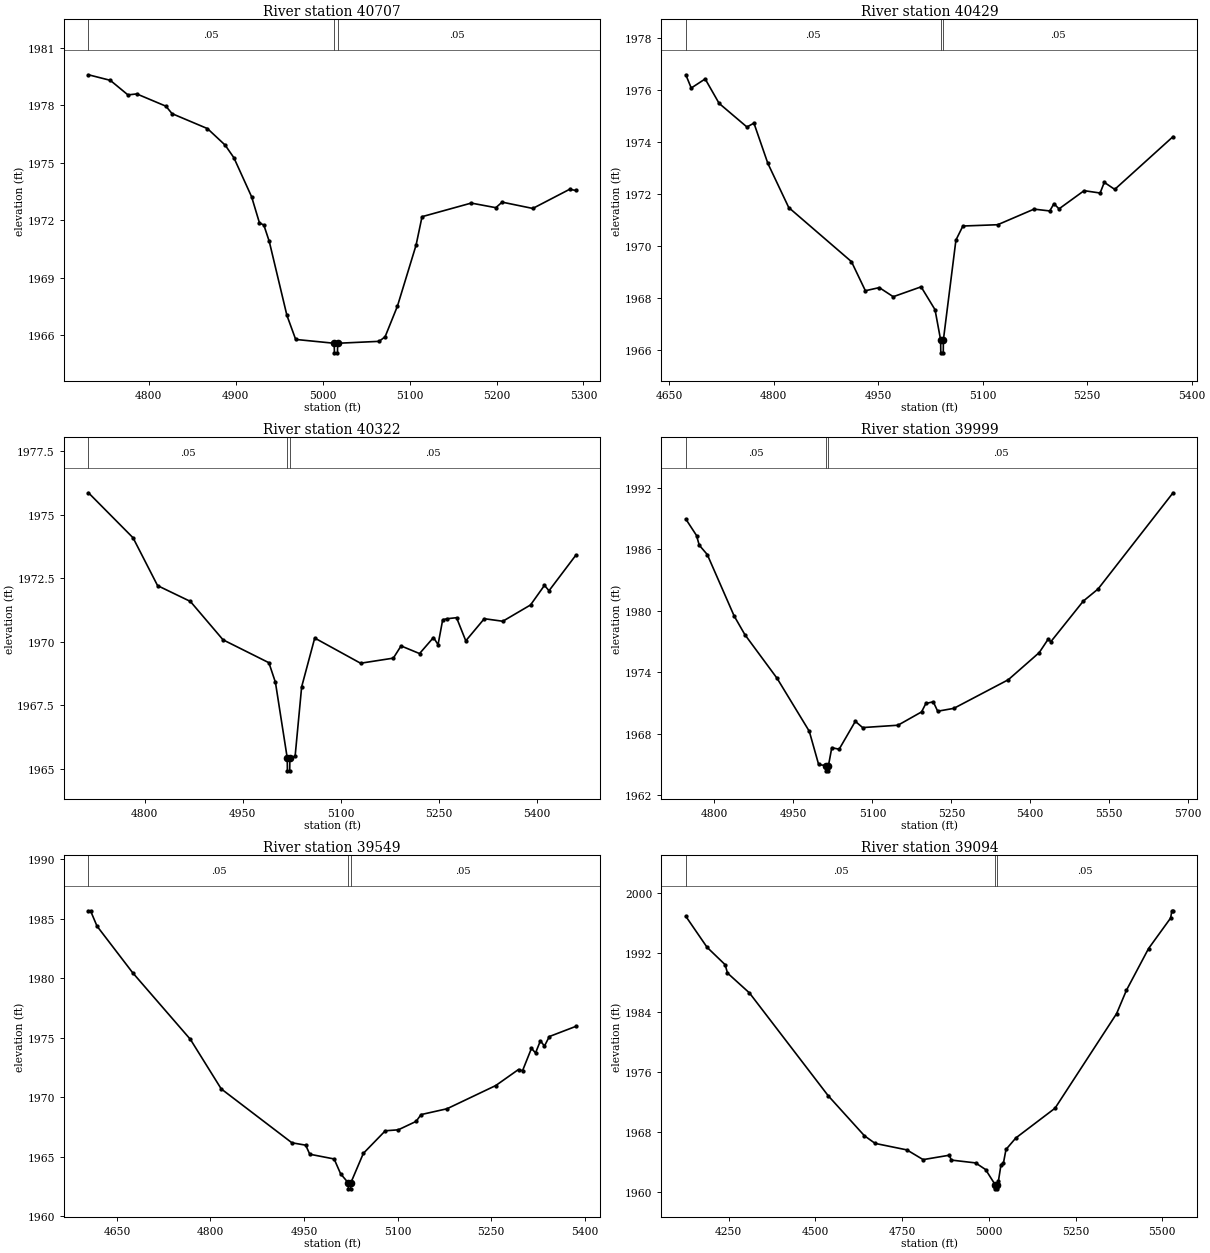
Type RM Length L Ch R = 1,40707,278,278,278
BEGIN DESCRIPTION:
Deadman 64 82.0
END DESCRIPTION:
XS GIS Cut Line= 3
      1658024.71      6855073.27      1658071.66      6855336.14
      1658274.85      6855548.03
#Sta/Elev= 30
  4730.5 1979.59  4755.6 1979.30  4775.9 1978.54  4786.1 1978.59  4819.6 1977.95
  4826.7 1977.56  4867.4 1976.78  4887.7 1975.92  4897.8 1975.26  4918.2 1973.22
  4927.2 1971.86  4932.3 1971.74  4938.5 1970.89  4958.8 1967.03  4968.9 1965.77
  5013.2 1965.57  5013.5 1965.07  5017.0 1965.07  5017.2 1965.57  5064.9 1965.67
  5071.8 1965.91  5086.0 1967.51  5107.4 1970.69  5114.3 1972.18  5170.9 1972.89
  5199.2 1972.65  5206.4 1972.94  5241.7 1972.61  5284.1 1973.61  5291.1 1973.55
#Mann=3,-1,0
  4730.5    0.05       0  5013.2    0.05       0  5017.2    0.05       0
Bank Sta=5013.2,5017.2
Exp/Cntr=0.3,0.1

Type RM Length L Ch R = 1,40429,107,107,107
BEGIN DESCRIPTION:
Mapping XS 85a0c4ad
END DESCRIPTION:
XS GIS Cut Line= 3
      1657933.80      6855230.19      1657938.16      6855717.78
      1658054.92      6855894.60
#Sta/Elev= 30
  4673.7 1976.58  4681.5 1976.07  4701.5 1976.42  4721.5 1975.48  4761.5 1974.57
  4771.5 1974.72  4791.5 1973.17  4821.5 1971.47  4911.5 1969.39  4931.5 1968.27
  4951.5 1968.39  4971.5 1968.04  5011.5 1968.42  5031.5 1967.54  5039.5 1966.38
  5039.8 1965.88  5043.3 1965.88  5043.5 1966.38  5061.5 1970.22  5071.5 1970.76
  5121.5 1970.81  5173.6 1971.41  5196.2 1971.34  5202.2 1971.62  5209.5 1971.42
  5245.5 1972.12  5268.5 1972.03  5274.5 1972.44  5289.5 1972.17  5373.2 1974.20
#Mann=3,-1,0
  4673.7    0.05       0  5039.5    0.05       0  5043.5    0.05       0
Bank Sta=5039.5,5043.5
Exp/Cntr=0.3,0.1

Type RM Length L Ch R = 1,40322,323,323,323
BEGIN DESCRIPTION:
Mapping XS dd5caab5
END DESCRIPTION:
XS GIS Cut Line= 3
      1657826.78      6855302.40      1657851.09      6855798.95
      1658028.15      6855972.53
#Sta/Elev= 30
  4714.2 1975.86  4782.4 1974.09  4819.9 1972.21  4870.0 1971.59  4920.0 1970.08
  4990.1 1969.18  5000.1 1968.41  5018.2 1965.43  5018.4 1964.93  5021.9 1964.93
  5022.2 1965.43  5030.2 1965.50  5040.2 1968.23  5060.2 1970.15  5130.3 1969.16
  5180.4 1969.36  5192.2 1969.84  5220.5 1969.54  5241.8 1970.17  5248.8 1969.89
  5255.9 1970.87  5262.9 1970.91  5277.1 1970.95  5291.2 1970.04  5319.5 1970.91
  5347.8 1970.81  5390.2 1971.45  5411.5 1972.22  5418.5 1972.01  5459.3 1973.40
#Mann=3,-1,0
  4714.2    0.05       0  5018.2    0.05       0  5022.2    0.05       0
Bank Sta=5018.2,5022.2
Exp/Cntr=0.3,0.1

Type RM Length L Ch R = 1,39999,450,450,450
BEGIN DESCRIPTION:
Deadman 64 81.0
END DESCRIPTION:
XS GIS Cut Line= 3
      1657454.96      6855787.99      1657705.00      6855838.00
      1658304.99      6856137.99
#Sta/Elev= 30
  4745.5 1988.97  4765.9 1987.36  4771.0 1986.42  4786.3 1985.50  4837.3 1979.50
  4857.7 1977.67  4918.9 1973.40  4980.1 1968.22  4997.9 1964.97  5012.5 1964.85
  5012.7 1964.35  5016.2 1964.35  5016.5 1964.85  5022.9 1966.62  5036.8 1966.46
  5067.6 1969.19  5081.5 1968.58  5148.6 1968.81  5193.4 1970.11  5201.7 1970.94
  5215.7 1971.10  5224.1 1970.18  5254.8 1970.46  5358.3 1973.26  5417.0 1975.91
  5433.7 1977.20  5439.3 1976.99  5500.8 1980.95  5528.8 1982.13  5671.3 1991.54
#Mann=3,-1,0
  4745.5    0.05       0  5012.5    0.05       0  5016.5    0.05       0
Bank Sta=5012.5,5016.5
Exp/Cntr=0.3,0.1

Type RM Length L Ch R = 1,39549,455,455,455
BEGIN DESCRIPTION:
Deadman 64 80.0
END DESCRIPTION:
XS GIS Cut Line= 3
      1657405.00      6855938.00      1657655.00      6856238.00
      1657954.98      6856487.98
#Sta/Elev= 30
  4604.4 1985.68  4607.7 1985.68  4618.1 1984.39  4675.3 1980.47  4767.8 1974.87
  4817.2 1970.71  4930.5 1966.18  4952.6 1965.98  4959.1 1965.22  4998.2 1964.82
  5008.6 1963.57  5020.9 1962.81  5021.2 1962.31  5024.7 1962.31  5024.9 1962.81
  5045.0 1965.29  5080.2 1967.19  5101.0 1967.27  5129.6 1967.98  5137.5 1968.55
  5179.1 1969.04  5257.2 1970.99  5293.7 1972.34  5300.2 1972.24  5314.5 1974.12
  5321.0 1973.73  5328.8 1974.75  5335.3 1974.31  5343.1 1975.11  5385.4 1975.96
#Mann=3,-1,0
  4604.4    0.05       0  5020.9    0.05       0  5024.9    0.05       0
Bank Sta=5020.9,5024.9
Exp/Cntr=0.3,0.1

Type RM Length L Ch R = 1,39094,437,437,437
BEGIN DESCRIPTION:
Deadman 64 79.0
END DESCRIPTION:
XS GIS Cut Line= 3
      1657254.99      6855787.97      1657605.00      6856588.00
      1658004.96      6856937.97
#Sta/Elev= 30
  4126.1 1996.87  4187.3 1992.73  4239.6 1990.39  4246.2 1989.28  4309.7 1986.61
  4536.6 1972.86  4641.1 1967.50  4671.9 1966.48  4763.5 1965.61  4810.3 1964.31
  4885.9 1964.90  4891.4 1964.25  4961.5 1963.87  4990.4 1962.98  5018.7 1960.90
  5018.9 1960.40  5022.4 1960.40  5022.7 1960.90  5027.3 1961.43  5034.9 1963.65
  5041.6 1963.80  5049.2 1965.67  5077.6 1967.21  5190.6 1971.19  5368.1 1983.85
  5396.5 1986.98  5460.1 1992.55  5523.7 1996.63  5527.5 1997.61  5530.8 1997.61
#Mann=3,-1,0
  4126.1    0.05       0  5018.7    0.05       0  5022.7    0.05       0
Bank Sta=5018.7,5022.7
Exp/Cntr=0.3,0.1

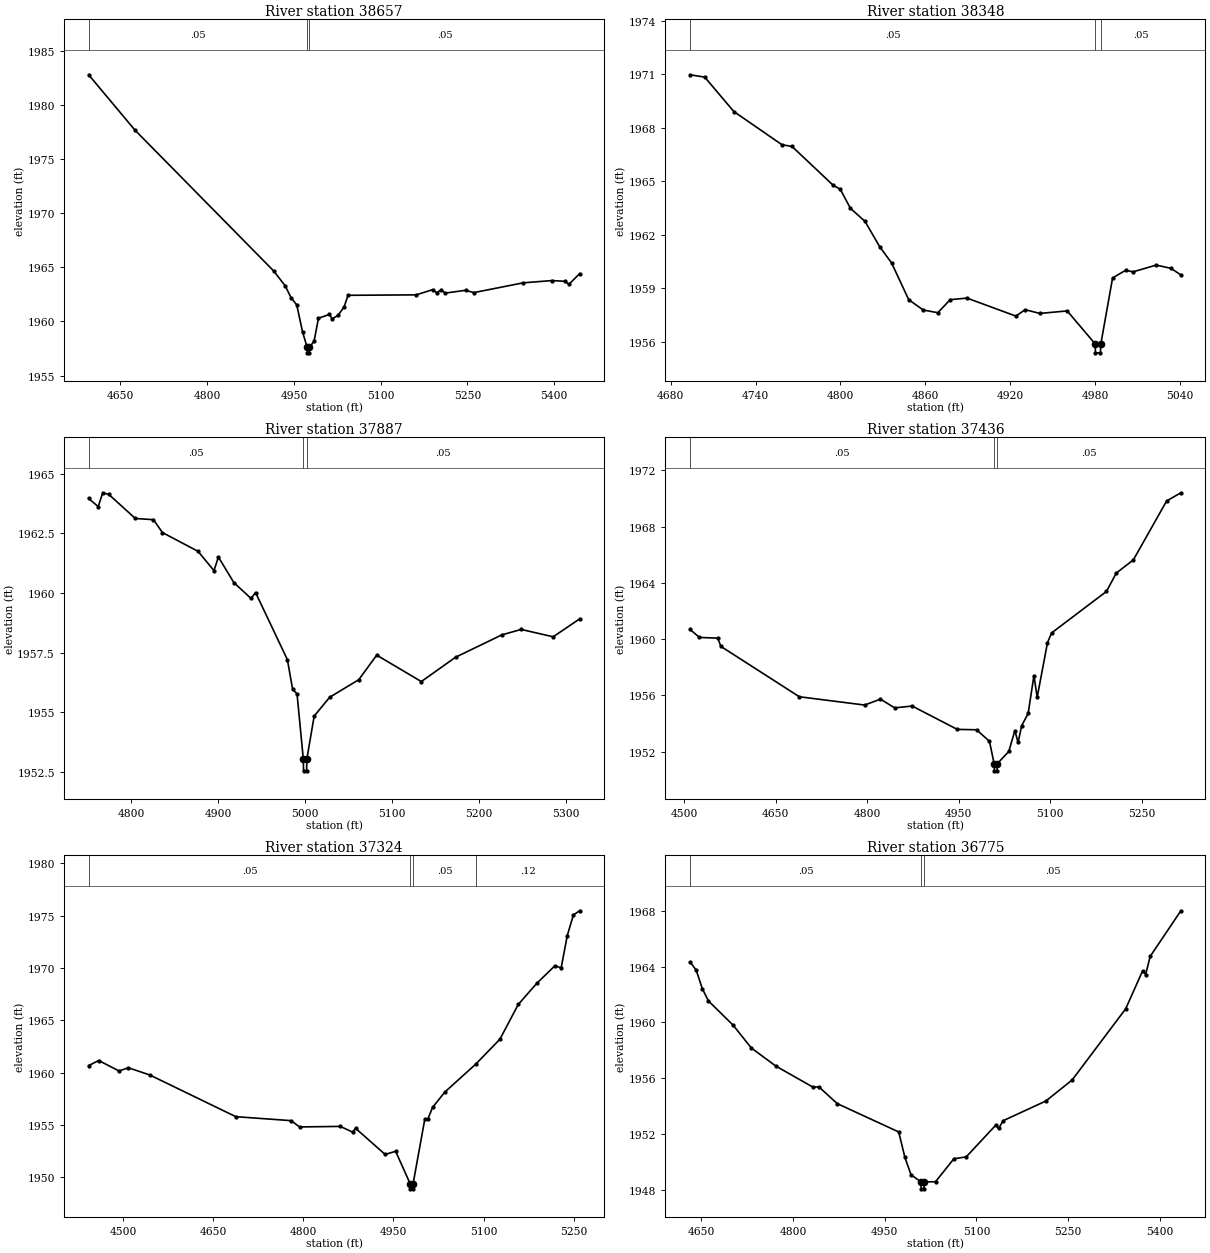
Type RM Length L Ch R = 1,38657,309,309,309
BEGIN DESCRIPTION:
Deadman 64 78.0
END DESCRIPTION:
XS GIS Cut Line= 4
      1657255.00      6856038.04      1657255.00      6856438.00
      1657225.58      6856532.13      1657504.93      6856743.87
#Sta/Elev= 30
  4595.0 1982.76  4675.0 1977.66  4915.0 1964.66  4935.0 1963.28  4945.0 1962.20
  4955.0 1961.52  4965.0 1959.03  4973.0 1957.60  4973.2 1957.10  4976.7 1957.10
  4977.0 1957.60  4985.0 1958.19  4992.5 1960.29  5011.2 1960.64  5016.4 1960.25
  5026.4 1960.55  5036.9 1961.35  5043.7 1962.41  5161.5 1962.45  5190.6 1962.94
  5196.9 1962.64  5205.2 1962.93  5211.5 1962.61  5246.9 1962.87  5261.4 1962.66
  5346.7 1963.56  5396.6 1963.77  5419.1 1963.70  5425.7 1963.42  5444.1 1964.40
#Mann=3,-1,0
  4595.0    0.05       0  4973.0    0.05       0  4977.0    0.05       0
Bank Sta=4973,4977
Exp/Cntr=0.3,0.1

Type RM Length L Ch R = 1,38348,461,461,461
BEGIN DESCRIPTION:
Mapping XS 94eb1c86
END DESCRIPTION:
XS GIS Cut Line= 2
      1657035.11      6856187.87      1656951.60      6856524.88
#Sta/Elev= 30
  4693.6 1970.97  4704.0 1970.84  4724.6 1968.91  4758.6 1967.05  4765.8 1966.95
  4794.8 1964.78  4799.9 1964.55  4807.1 1963.48  4817.4 1962.75  4827.7 1961.34
  4836.2 1960.42  4848.3 1958.36  4858.6 1957.78  4868.9 1957.63  4877.6 1958.36
  4889.5 1958.45  4924.1 1957.44  4930.7 1957.80  4941.0 1957.59  4960.4 1957.73
  4980.2 1955.88  4980.4 1955.38  4983.9 1955.38  4984.2 1955.88  4992.5 1959.58
  5001.8 1960.01  5006.9 1959.92  5023.4 1960.30  5033.7 1960.12  5040.8 1959.75
#Mann=3,-1,0
  4693.6    0.05       0  4980.2    0.05       0  4984.2    0.05       0
Bank Sta=4980.2,4984.2
Exp/Cntr=0.3,0.1

Type RM Length L Ch R = 1,37887,451,451,451
BEGIN DESCRIPTION:
Mapping XS a2b4568b
END DESCRIPTION:
XS GIS Cut Line= 3
      1656576.77      6856045.43      1656667.06      6856434.36
      1656815.12      6856507.46
#Sta/Elev= 30
  4751.4 1963.97  4762.4 1963.63  4767.6 1964.21  4774.6 1964.14  4805.1 1963.13
  4825.9 1963.08  4836.2 1962.54  4877.2 1961.75  4895.5 1960.94  4900.6 1961.51
  4918.3 1960.44  4938.1 1959.77  4943.3 1960.02  4979.9 1957.20  4985.9 1955.96
  4991.0 1955.76  4998.2 1953.03  4998.5 1952.53  5002.0 1952.53  5002.3 1953.03
  5010.7 1954.83  5028.5 1955.62  5062.0 1956.36  5082.6 1957.39  5133.9 1956.28
  5173.2 1957.30  5226.4 1958.24  5248.7 1958.47  5285.5 1958.16  5315.8 1958.91
#Mann=3,-1,0
  4751.4    0.05       0  4998.2    0.05       0  5002.3    0.05       0
Bank Sta=4998.2,5002.3
Exp/Cntr=0.3,0.1

Type RM Length L Ch R = 1,37436,112,112,112
BEGIN DESCRIPTION:
Mapping XS 00a32d5d
END DESCRIPTION:
XS GIS Cut Line= 4
      1656440.61      6856102.86      1656367.69      6856438.78
      1656448.42      6856675.76      1656404.16      6856881.45
#Sta/Elev= 30
  4509.4 1960.69  4524.9 1960.12  4554.9 1960.07  4560.1 1959.48  4688.6 1955.90
  4795.6 1955.31  4821.6 1955.73  4844.8 1955.11  4873.5 1955.24  4947.4 1953.58
  4979.1 1953.55  5000.2 1952.73  5007.9 1951.13  5008.3 1950.63  5012.6 1950.63
  5012.9 1951.13  5031.9 1952.01  5041.8 1953.49  5047.1 1952.65  5053.0 1953.84
  5063.6 1954.71  5073.1 1957.41  5078.4 1955.86  5095.3 1959.75  5102.0 1960.44
  5191.9 1963.39  5208.1 1964.70  5236.1 1965.64  5290.6 1969.83  5313.9 1970.41
#Mann=3,-1,0
  4509.4    0.05       0  5007.9    0.05       0  5012.9    0.05       0
Bank Sta=5007.9,5012.9
Exp/Cntr=0.3,0.1

Type RM Length L Ch R = 1,37324,549,549,549
BEGIN DESCRIPTION:
Deadman 64 75.0
END DESCRIPTION:
XS GIS Cut Line= 3
      1656424.00      6856038.56      1656305.00      6856588.00
      1656255.01      6856837.97
#Sta/Elev= 30
  4442.6 1960.67  4459.4 1961.15  4493.2 1960.15  4508.6 1960.46  4544.3 1959.77
  4687.6 1955.78  4779.7 1955.40  4793.6 1954.80  4861.5 1954.85  4881.8 1954.31
  4886.9 1954.67  4936.1 1952.17  4953.6 1952.47  4977.7 1949.38  4978.0 1948.88
  4982.3 1948.88  4982.7 1949.38  5002.2 1955.56  5007.3 1955.56  5015.0 1956.66
  5035.4 1958.13  5087.4 1960.83  5127.2 1963.19  5157.7 1966.51  5188.3 1968.52
  5218.9 1970.22  5229.1 1970.00  5239.3 1973.10  5249.5 1975.07  5259.7 1975.47
#Mann=4,-1,0
  4442.6    0.05       0  4977.7    0.03       0  4982.7    0.05       0
  5087.4    0.12       0
Bank Sta=4977.7,4982.7
Exp/Cntr=0.3,0.1

Type RM Length L Ch R = 1,36775,408,408,408
BEGIN DESCRIPTION:
Deadman 64 74.0
END DESCRIPTION:
XS GIS Cut Line= 3
      1655955.00      6855887.99      1655919.78      6856266.91
      1655955.00      6856687.98
#Sta/Elev= 30
  4631.4 1964.33  4641.5 1963.75  4651.5 1962.42  4661.5 1961.54  4701.7 1959.81
  4731.8 1958.16  4772.0 1956.86  4832.3 1955.36  4842.3 1955.37  4872.4 1954.17
  4972.9 1952.14  4982.9 1950.33  4993.0 1949.07  5009.3 1948.56  5009.7 1948.06
  5014.2 1948.06  5014.7 1948.56  5033.1 1948.57  5063.2 1950.22  5083.3 1950.35
  5131.5 1952.62  5136.5 1952.39  5143.5 1952.94  5213.7 1954.36  5256.7 1955.87
  5344.2 1960.97  5371.9 1963.69  5376.9 1963.43  5384.3 1964.73  5434.5 1968.00
#Mann=3,-1,0
  4631.4    0.05       0  5009.3    0.05       0  5014.7    0.05       0
Bank Sta=5009.3,5014.7
Exp/Cntr=0.3,0.1

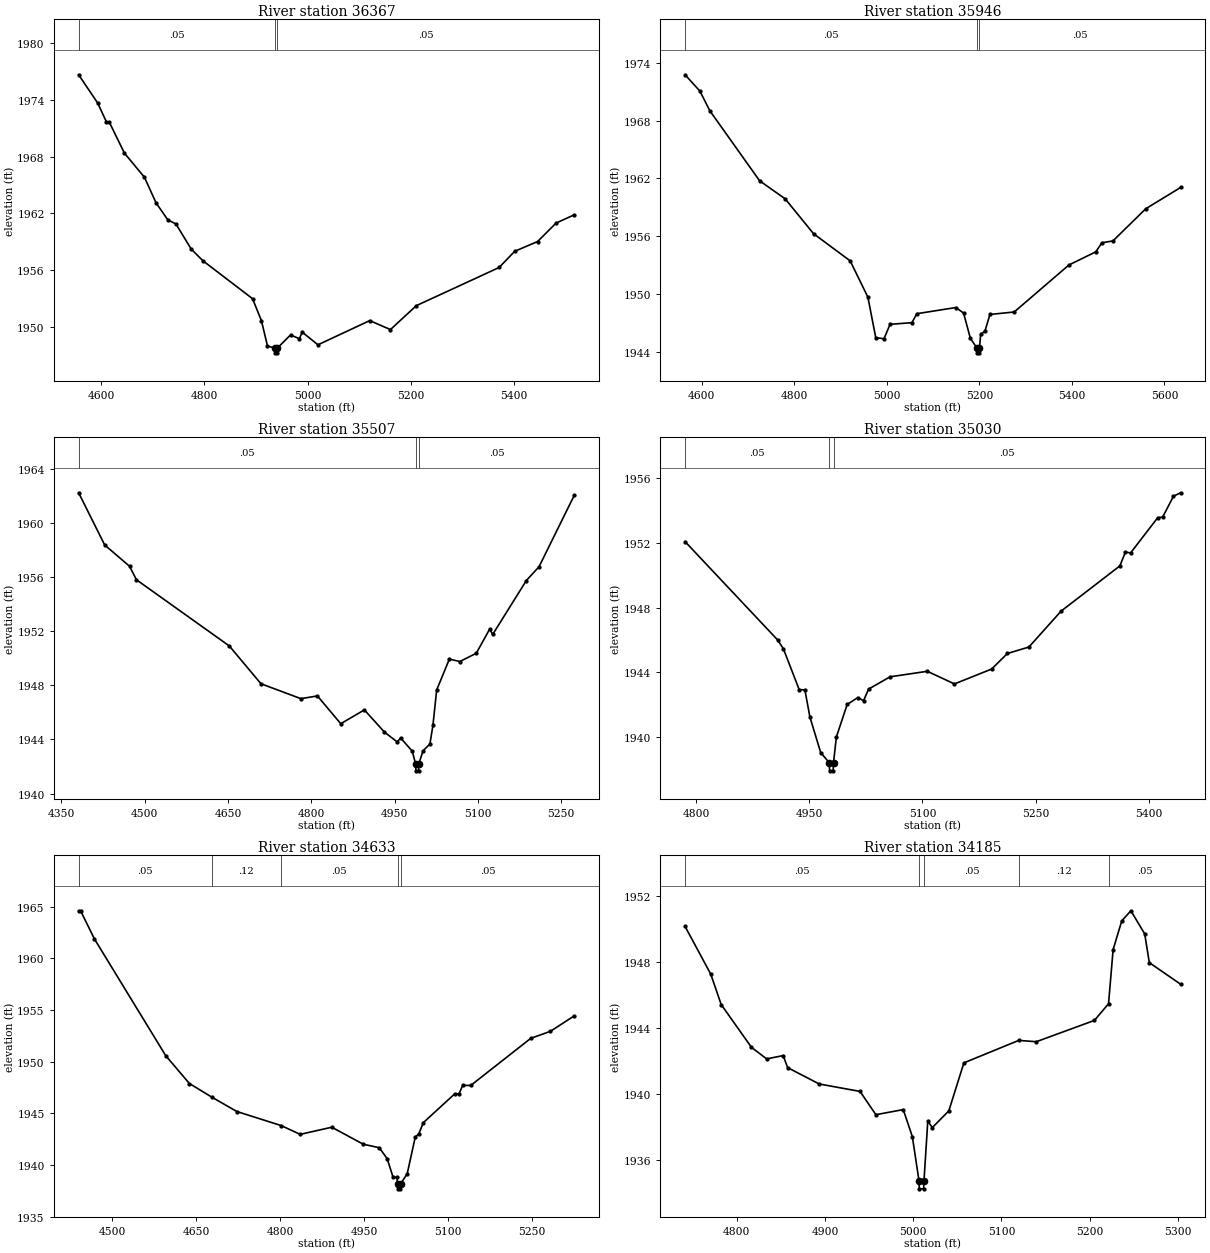
Type RM Length L Ch R = 1,36367,421,421,421
BEGIN DESCRIPTION:
Deadman 64 73.0
END DESCRIPTION:
XS GIS Cut Line= 3
      1655755.02      6855737.96      1655562.90      6856139.22
      1655524.71      6856653.02
#Sta/Elev= 30
  4556.4 1976.65  4593.2 1973.67  4610.3 1971.66  4615.9 1971.63  4645.1 1968.36
  4683.9 1965.81  4706.5 1963.09  4729.2 1961.30  4744.9 1960.87  4774.5 1958.21
  4797.2 1956.97  4893.4 1952.96  4910.5 1950.64  4922.3 1947.96  4936.0 1947.73
  4936.4 1947.23  4941.0 1947.23  4941.4 1947.73  4966.9 1949.12  4984.1 1948.73
  4989.6 1949.42  5020.1 1948.08  5120.4 1950.64  5160.5 1949.69  5210.6 1952.22
  5371.1 1956.26  5401.2 1957.97  5445.7 1959.01  5481.4 1960.96  5516.5 1961.83
#Mann=3,-1,0
  4556.4    0.05       0  4936.0    0.05       0  4941.4    0.05       0
Bank Sta=4936,4941.4
Exp/Cntr=0.3,0.1

Type RM Length L Ch R = 1,35946,439,439,439
BEGIN DESCRIPTION:
Deadman 64 72.0
END DESCRIPTION:
XS GIS Cut Line= 3
      1655355.01      6855637.98      1655205.00      6856038.00
      1655406.63      6856649.60
#Sta/Elev= 30
  4563.9 1972.75  4596.0 1971.05  4617.3 1969.02  4725.0 1961.75  4780.2 1959.88
  4841.6 1956.26  4920.8 1953.44  4959.1 1949.67  4976.0 1945.48  4993.8 1945.36
  5007.0 1946.86  5054.3 1947.03  5064.8 1947.96  5149.1 1948.60  5165.8 1948.03
  5180.7 1945.39  5194.8 1944.40  5195.3 1943.90  5199.9 1943.90  5200.3 1944.40
  5202.8 1945.81  5212.2 1946.17  5222.8 1947.88  5275.4 1948.14  5393.4 1953.01
  5451.7 1954.38  5464.9 1955.32  5488.7 1955.51  5559.7 1958.85  5635.1 1961.06
#Mann=3,-1,0
  4563.9    0.05       0  5194.8    0.05       0  5200.3    0.05       0
Bank Sta=5194.8,5200.3
Exp/Cntr=0.3,0.1

Type RM Length L Ch R = 1,35507,477,477,477
BEGIN DESCRIPTION:
Deadman 64 71.0
END DESCRIPTION:
XS GIS Cut Line= 3
      1654705.23      6855871.83      1655055.00      6856388.00
      1655155.01      6856638.02
#Sta/Elev= 30
  4380.9 1962.21  4427.8 1958.36  4472.7 1956.78  4485.0 1955.79  4652.4 1950.90
  4709.4 1948.11  4781.3 1947.01  4811.1 1947.21  4853.2 1945.16  4895.7 1946.18
  4931.9 1944.54  4955.0 1943.81  4961.0 1944.11  4982.0 1943.13  4988.1 1942.18
  4988.6 1941.68  4993.3 1941.68  4993.7 1942.18  5001.4 1943.16  5013.8 1943.66
  5019.2 1945.03  5026.0 1947.65  5048.8 1949.93  5067.7 1949.75  5097.3 1950.36
  5121.5 1952.15  5126.9 1951.75  5187.5 1955.73  5210.4 1956.75  5273.7 1962.01
#Mann=3,-1,0
  4380.9    0.05       0  4988.1    0.05       0  4993.7    0.05       0
Bank Sta=4988.1,4993.7
Exp/Cntr=0.3,0.1

Type RM Length L Ch R = 1,35030,397,397,397
BEGIN DESCRIPTION:
Mapping XS 0e2ed83b
END DESCRIPTION:
XS GIS Cut Line= 2
      1654455.23      6856284.17      1654947.42      6856719.06
#Sta/Elev= 30
  4785.4 1952.07  4908.2 1945.99  4915.7 1945.45  4936.6 1942.93  4944.2 1942.91
  4950.8 1941.24  4965.1 1939.04  4976.5 1938.41  4976.9 1937.91  4981.6 1937.91
  4982.1 1938.41  4985.9 1940.00  5000.2 1942.01  5014.4 1942.44  5021.9 1942.24
  5028.6 1942.96  5057.1 1943.72  5106.4 1944.06  5142.4 1943.28  5191.7 1944.20
  5212.6 1945.16  5241.1 1945.56  5283.8 1947.78  5361.6 1950.57  5369.1 1951.43
  5375.8 1951.37  5411.8 1953.55  5418.4 1953.59  5432.7 1954.88  5442.2 1955.09
#Mann=3,-1,0
  4785.4    0.05       0  4976.5    0.05       0  4982.1    0.05       0
Bank Sta=4976.5,4982.1
Exp/Cntr=0.3,0.1

Type RM Length L Ch R = 1,34633,448,448,448
BEGIN DESCRIPTION:
Deadman 64 69.0
END DESCRIPTION:
XS GIS Cut Line= 3
      1654105.01      6856388.01      1654505.00      6856788.00
      1654704.98      6857037.97
#Sta/Elev= 30
  4439.6 1964.59  4443.1 1964.59  4467.9 1961.86  4595.2 1950.58  4637.6 1947.88
  4677.4 1946.57  4722.4 1945.17  4801.7 1943.81  4835.6 1942.96  4892.1 1943.65
  4948.7 1942.00  4977.0 1941.67  4991.1 1940.61  5001.7 1938.81  5008.5 1938.81
  5009.6 1938.19  5010.1 1937.69  5014.9 1937.69  5015.3 1938.19  5026.9 1939.14
  5041.3 1942.69  5047.7 1943.01  5055.7 1944.09  5111.7 1946.87  5119.7 1946.89
  5126.1 1947.70  5140.5 1947.69  5247.8 1952.25  5283.0 1952.93  5325.4 1954.42
#Mann=5,-1,0
  4439.6    0.05       0  4677.4    0.12       0  4801.7    0.05       0
  5009.6    0.05       0  5015.3    0.05       0
Bank Sta=5009.6,5015.3
Exp/Cntr=0.3,0.1

Type RM Length L Ch R = 1,34185,436,436,436
BEGIN DESCRIPTION:
Mapping XS ce2b2ade
END DESCRIPTION:
XS GIS Cut Line= 2
      1654121.93      6856638.39      1654259.95      6857182.66
#Sta/Elev= 30
  4741.6 1950.17  4770.7 1947.28  4782.5 1945.44  4816.8 1942.85  4834.0 1942.15
  4852.7 1942.35  4857.8 1941.62  4893.6 1940.63  4939.8 1940.18  4957.8 1938.77
  4988.8 1939.08  4999.1 1937.44  5006.6 1934.78  5007.0 1934.28  5011.8 1934.28
  5012.3 1934.78  5016.6 1938.39  5021.7 1937.99  5040.4 1939.00  5057.5 1941.91
  5119.7 1943.27  5139.5 1943.19  5205.4 1944.48  5221.4 1945.49  5226.6 1948.77
  5236.4 1950.51  5246.7 1951.12  5262.4 1949.72  5267.6 1947.98  5303.1 1946.67
#Mann=5,-1,0
  4741.6    0.05       0  5006.6    0.05       0  5012.3    0.05       0
  5119.7    0.12       0  5221.4    0.05       0
Bank Sta=5006.6,5012.3
Exp/Cntr=0.3,0.1

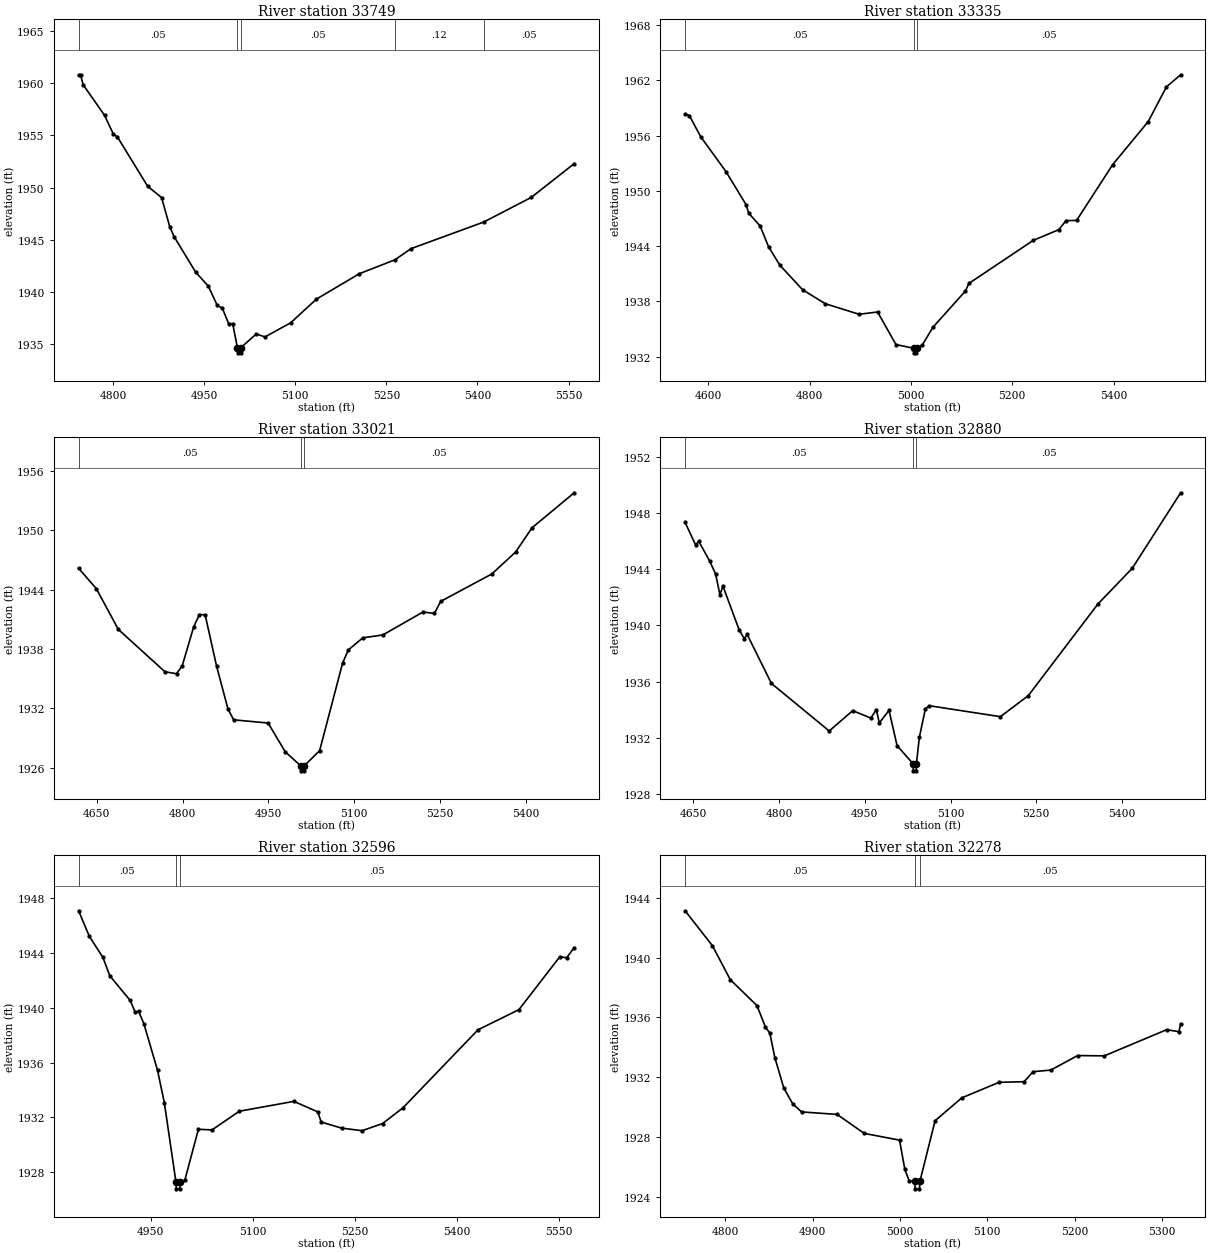
Type RM Length L Ch R = 1,33749,414,414,414
BEGIN DESCRIPTION:
Deadman 64 67.0
END DESCRIPTION:
XS GIS Cut Line= 3
      1653704.98      6856887.97      1653855.00      6857088.00
      1654254.98      6857487.98
#Sta/Elev= 30
  4743.5 1960.78  4746.7 1960.78  4750.8 1959.84  4786.2 1956.90  4800.8 1955.09
  4807.1 1954.86  4857.1 1950.12  4880.0 1949.04  4893.5 1946.25  4900.8 1945.29
  4936.2 1941.90  4957.1 1940.56  4971.7 1938.72  4980.0 1938.47  4990.4 1936.98
  4997.1 1936.98  5004.8 1934.69  5005.3 1934.19  5010.1 1934.19  5010.6 1934.69
  5036.0 1936.00  5050.1 1935.71  5092.5 1937.06  5135.0 1939.33  5205.7 1941.76
  5264.3 1943.09  5290.5 1944.15  5410.4 1946.70  5488.5 1949.05  5559.2 1952.28
#Mann=5,-1,0
  4743.5    0.05       0  5004.8    0.05       0  5010.6    0.05       0
  5264.3    0.12       0  5410.4    0.05       0
Bank Sta=5004.8,5010.6
Exp/Cntr=0.3,0.1

Type RM Length L Ch R = 1,33335,314,314,314
BEGIN DESCRIPTION:
Deadman 64 66.0
END DESCRIPTION:
XS GIS Cut Line= 3
      1653454.98      6857037.97      1653655.00      6857438.00
      1654005.03      6857838.03
#Sta/Elev= 30
  4553.8 1958.36  4562.2 1958.19  4584.6 1955.89  4634.9 1952.07  4674.0 1948.52
  4679.6 1947.57  4702.0 1946.19  4718.7 1943.92  4741.1 1941.92  4785.8 1939.26
  4830.6 1937.74  4897.6 1936.59  4934.0 1936.84  4970.3 1933.30  5005.3 1932.90
  5005.7 1932.40  5010.6 1932.40  5011.1 1932.90  5022.4 1933.25  5043.3 1935.18
  5107.4 1939.11  5114.5 1939.95  5241.7 1944.63  5292.0 1945.79  5306.2 1946.77
  5327.1 1946.79  5398.3 1952.85  5468.5 1957.53  5504.6 1961.31  5532.6 1962.62
#Mann=3,-1,0
  4553.8    0.05       0  5005.3    0.03       0  5011.1    0.05       0
Bank Sta=5005.3,5011.1
Exp/Cntr=0.3,0.1

Type RM Length L Ch R = 1,33021,141,141,141
BEGIN DESCRIPTION:
Mapping XS 6d5b4ae7
END DESCRIPTION:
XS GIS Cut Line= 3
      1653411.96      6857207.01      1653401.55      6857592.43
      1653438.00      6858071.58
#Sta/Elev= 30
  4618.4 1946.17  4649.4 1944.10  4687.8 1939.98  4769.4 1935.69  4789.5 1935.50
  4799.5 1936.31  4819.5 1940.24  4829.5 1941.48  4839.5 1941.46  4859.5 1936.27
  4879.5 1931.91  4889.5 1930.83  4949.5 1930.51  4979.5 1927.60  5006.7 1926.17
  5007.1 1925.67  5012.0 1925.67  5012.5 1926.17  5039.6 1927.71  5079.8 1936.58
  5089.8 1937.91  5115.1 1939.13  5150.0 1939.42  5220.2 1941.74  5240.2 1941.60
  5251.2 1942.82  5340.5 1945.59  5382.3 1947.82  5410.7 1950.26  5484.5 1953.81
#Mann=3,-1,0
  4618.4    0.05       0  5006.7    0.05       0  5012.5    0.05       0
Bank Sta=5006.7,5012.5
Exp/Cntr=0.3,0.1

Type RM Length L Ch R = 1,32880,284,284,284
BEGIN DESCRIPTION:
Mapping XS e357284a
END DESCRIPTION:
XS GIS Cut Line= 4
      1653374.52      6857206.09      1653335.47      6857372.73
      1653246.92      6857625.33      1653280.77      6858052.37
#Sta/Elev= 30
  4635.5 1947.35  4654.1 1945.72  4659.2 1946.02  4678.5 1944.59  4688.8 1943.68
  4696.5 1942.19  4701.7 1942.81  4729.9 1939.71  4739.0 1939.06  4744.1 1939.36
  4786.6 1935.87  4887.7 1932.48  4928.8 1933.93  4960.6 1933.40  4970.1 1934.00
  4975.4 1933.06  4992.4 1933.95  5006.4 1931.44  5034.5 1930.14  5035.0 1929.64
  5039.9 1929.64  5040.3 1930.14  5045.4 1932.02  5056.0 1934.06  5063.1 1934.28
  5187.3 1933.50  5236.1 1935.00  5357.9 1941.53  5418.1 1944.08  5502.7 1949.46
#Mann=3,-1,0
  4635.5    0.05       0  5034.5    0.05       0  5040.3    0.05       0
Bank Sta=5034.5,5040.3
Exp/Cntr=0.3,0.1

Type RM Length L Ch R = 1,32596,318,318,318
BEGIN DESCRIPTION:
Mapping XS 8f6755d0
END DESCRIPTION:
XS GIS Cut Line= 2
      1653046.41      6857302.38      1652991.71      6858029.02
#Sta/Elev= 30
  4843.8 1947.07  4859.5 1945.21  4879.5 1943.67  4889.6 1942.33  4919.6 1940.53
  4926.9 1939.68  4931.9 1939.75  4939.7 1938.84  4959.8 1935.44  4969.8 1933.08
  4986.9 1927.29  4987.4 1926.79  4992.3 1926.79  4992.8 1927.29  4999.9 1927.41
  5019.9 1931.13  5040.0 1931.09  5080.1 1932.45  5160.3 1933.17  5195.5 1932.40
  5200.5 1931.66  5230.5 1931.22  5260.6 1931.03  5290.7 1931.55  5320.8 1932.70
  5431.1 1938.39  5491.3 1939.86  5551.4 1943.72  5561.4 1943.64  5572.5 1944.38
#Mann=3,-1,0
  4843.8    0.05       0  4986.9    0.05       0  4992.8    0.05       0
Bank Sta=4986.9,4992.8
Exp/Cntr=0.3,0.1

Type RM Length L Ch R = 1,32278,314,314,314
BEGIN DESCRIPTION:
Mapping XS 82cf8736
END DESCRIPTION:
XS GIS Cut Line= 2
      1652788.58      6857297.24      1652679.37      6857853.72
#Sta/Elev= 30
  4754.2 1943.14  4785.5 1940.80  4805.9 1938.53  4836.5 1936.79  4846.1 1935.36
  4851.2 1934.95  4856.9 1933.31  4867.1 1931.29  4877.3 1930.22  4887.5 1929.68
  4928.2 1929.51  4959.2 1928.24  4999.6 1927.79  5005.6 1925.85  5010.7 1925.06
  5017.0 1925.03  5017.5 1924.53  5022.4 1924.53  5022.9 1925.03  5040.3 1929.09
  5070.9 1930.62  5113.5 1931.66  5142.2 1931.70  5152.4 1932.37  5172.8 1932.48
  5203.4 1933.45  5233.9 1933.43  5305.3 1935.18  5319.3 1935.05  5321.3 1935.58
#Mann=3,-1,0
  4754.2    0.05       0  5017.0    0.05       0  5022.9    0.05       0
Bank Sta=5017,5022.9
Exp/Cntr=0.3,0.1

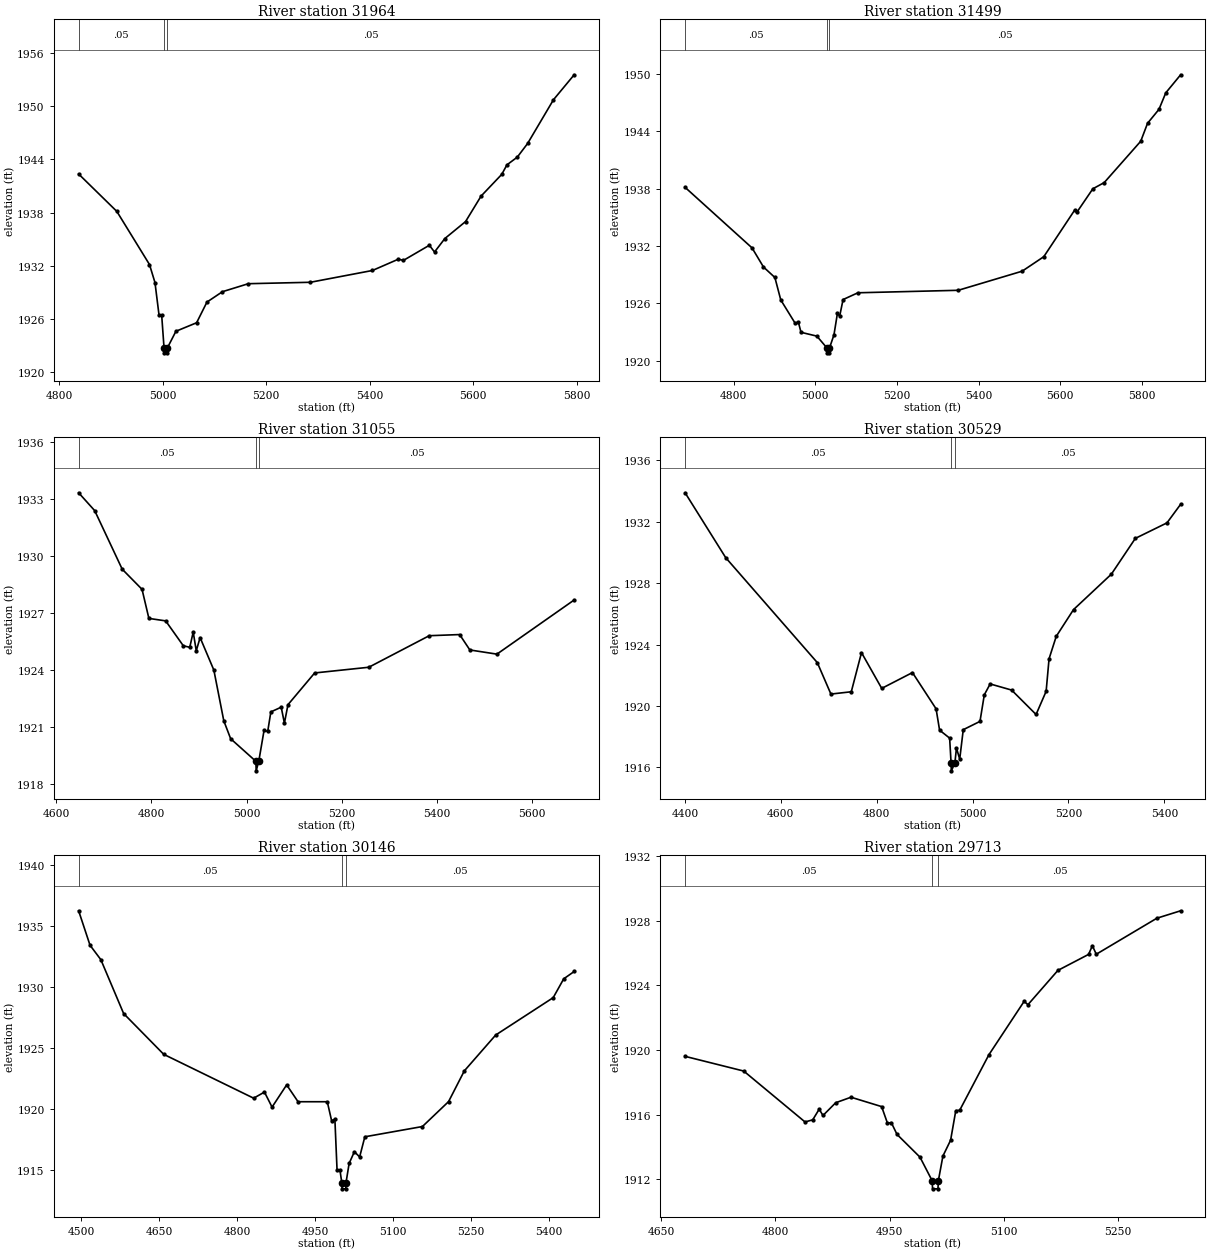
Type RM Length L Ch R = 1,31964,465,465,465
BEGIN DESCRIPTION:
Deadman 64 63.0
END DESCRIPTION:
XS GIS Cut Line= 3
      1652555.00      6857187.99      1652505.00      6857338.00
      1652505.00      6858137.98
#Sta/Elev= 30
  4837.2 1942.34  4911.0 1938.13  4974.2 1932.14  4984.8 1930.11  4992.7 1926.42
  4997.8 1926.42  5002.4 1922.69  5002.8 1922.19  5007.8 1922.19  5008.3 1922.69
  5025.3 1924.62  5065.3 1925.58  5085.3 1927.91  5115.3 1929.08  5165.3 1929.98
  5285.3 1930.14  5405.3 1931.47  5455.3 1932.74  5465.3 1932.61  5515.3 1934.31
  5525.3 1933.55  5545.3 1935.07  5585.3 1936.98  5615.3 1939.85  5655.3 1942.30
  5665.3 1943.37  5685.3 1944.24  5705.3 1945.78  5755.3 1950.71  5795.3 1953.52
#Mann=3,-1,0
  4837.2    0.05       0  5002.4    0.05       0  5008.3    0.05       0
Bank Sta=5002.4,5008.3
Exp/Cntr=0.3,0.1

Type RM Length L Ch R = 1,31499,444,444,444
BEGIN DESCRIPTION:
Deadman 64 62.0
END DESCRIPTION:
XS GIS Cut Line= 3
      1652305.00      6857088.00      1652055.00      6857288.00
      1652455.01      6858088.01
#Sta/Elev= 30
  4680.7 1938.14  4844.8 1931.80  4872.8 1929.80  4900.8 1928.70  4915.2 1926.35
  4950.4 1923.91  4958.4 1924.02  4964.8 1922.96  5003.7 1922.56  5028.6 1921.31
  5029.1 1920.81  5034.1 1920.81  5034.6 1921.31  5045.6 1922.70  5054.0 1924.93
  5059.6 1924.66  5067.9 1926.39  5104.3 1927.10  5350.2 1927.36  5506.8 1929.36
  5559.9 1930.88  5635.3 1935.74  5640.9 1935.53  5680.1 1937.99  5708.0 1938.64
  5797.5 1942.97  5814.2 1944.85  5842.2 1946.31  5858.9 1948.04  5895.3 1949.93
#Mann=3,-1,0
  4680.7    0.05       0  5028.6    0.05       0  5034.6    0.05       0
Bank Sta=5028.6,5034.6
Exp/Cntr=0.3,0.1

Type RM Length L Ch R = 1,31055,526,526,526
BEGIN DESCRIPTION:
Deadman 64 61.0
END DESCRIPTION:
XS GIS Cut Line= 3
      1651929.23      6856974.28      1651655.00      6857188.00
      1652114.08      6857708.63
#Sta/Elev= 30
  4646.9 1933.33  4680.7 1932.39  4738.5 1929.31  4780.2 1928.25  4794.6 1926.72
  4829.9 1926.59  4867.0 1925.28  4880.5 1925.20  4887.8 1926.00  4894.2 1925.02
  4902.3 1925.71  4931.2 1924.00  4952.1 1921.33  4966.5 1920.39  5019.6 1919.20
  5020.1 1918.70  5025.6 1919.20  5036.8 1920.84  5044.4 1920.77  5051.0 1921.80
  5072.8 1922.05  5079.5 1921.21  5087.0 1922.18  5143.1 1923.85  5256.9 1924.15
  5384.0 1925.81  5447.9 1925.87  5469.4 1925.06  5526.3 1924.84  5688.7 1927.69
#Mann=3,-1,0
  4646.9    0.05       0  5019.6    0.05       0  5025.6    0.05       0
Bank Sta=5019.6,5025.6
Exp/Cntr=0.3,0.1

Type RM Length L Ch R = 1,30529,383,383,383
BEGIN DESCRIPTION:
Deadman 64 60.0
END DESCRIPTION:
XS GIS Cut Line= 3
      1651055.00      6857188.00      1651498.22      6857598.59
      1651854.97      6857837.98
#Sta/Elev= 30
  4400.2 1933.89  4485.0 1929.66  4676.0 1922.83  4704.4 1920.78  4746.9 1920.93
  4768.2 1923.48  4810.4 1921.15  4874.5 1922.18  4923.8 1919.82  4931.1 1918.43
  4952.1 1917.91  4955.1 1916.28  4955.6 1915.78  4963.0 1916.28  4966.3 1917.27
  4973.1 1916.54  4980.5 1918.46  5015.4 1919.00  5024.4 1920.73  5036.6 1921.44
  5081.4 1921.04  5132.4 1919.45  5153.4 1920.96  5159.5 1923.08  5174.5 1924.54
  5210.5 1926.28  5289.5 1928.59  5339.5 1930.92  5405.5 1931.93  5434.0 1933.14
#Mann=3,-1,0
  4400.2    0.05       0  4955.1    0.05       0  4963.0    0.05       0
Bank Sta=4955.1,4963
Exp/Cntr=0.3,0.1

Type RM Length L Ch R = 1,30146,433,433,433
BEGIN DESCRIPTION:
Deadman 64 59.0
END DESCRIPTION:
XS GIS Cut Line= 3
      1650854.99      6857587.99      1651255.00      6857888.00
      1651705.02      6857838.00
#Sta/Elev= 30
  4495.5 1936.24  4517.4 1933.42  4538.2 1932.24  4582.0 1927.83  4659.1 1924.49
  4832.0 1920.90  4852.8 1921.40  4867.4 1920.17  4895.5 1921.99  4917.4 1920.61
  4973.6 1920.61  4982.0 1919.04  4988.2 1919.19  4992.4 1915.00  4998.0 1915.00
  5001.5 1913.98  5002.0 1913.48  5009.1 1913.48  5009.6 1913.98  5015.6 1915.56
  5025.7 1916.52  5035.8 1916.09  5045.8 1917.74  5156.5 1918.58  5206.8 1920.62
  5237.0 1923.13  5297.4 1926.07  5408.0 1929.13  5428.2 1930.67  5448.3 1931.27
#Mann=3,-1,0
  4495.5    0.05       0  5001.5    0.05       0  5009.6    0.05       0
Bank Sta=5001.5,5009.6
Exp/Cntr=0.3,0.1

Type RM Length L Ch R = 1,29713,431,431,431
BEGIN DESCRIPTION:
Mapping XS 4ac71870
END DESCRIPTION:
XS GIS Cut Line= 2
      1651038.51      6858252.78      1651685.17      6858326.04
#Sta/Elev= 30
  4681.4 1919.60  4758.4 1918.69  4838.9 1915.54  4849.0 1915.67  4857.5 1916.33
  4862.5 1915.94  4879.2 1916.73  4899.3 1917.07  4939.5 1916.49  4947.2 1915.46
  4952.2 1915.50  4959.7 1914.77  4989.9 1913.36  5005.9 1911.90  5006.4 1911.40
  5013.5 1911.40  5014.0 1911.90  5020.0 1913.43  5030.1 1914.41  5036.9 1916.24
  5042.0 1916.26  5080.4 1919.70  5126.6 1923.00  5131.7 1922.80  5171.0 1924.92
  5211.3 1925.91  5216.3 1926.45  5221.4 1925.92  5301.0 1928.15  5332.2 1928.61
#Mann=3,-1,0
  4681.4    0.05       0  5005.9    0.05       0  5014.0    0.05       0
Bank Sta=5005.9,5014
Exp/Cntr=0.3,0.1