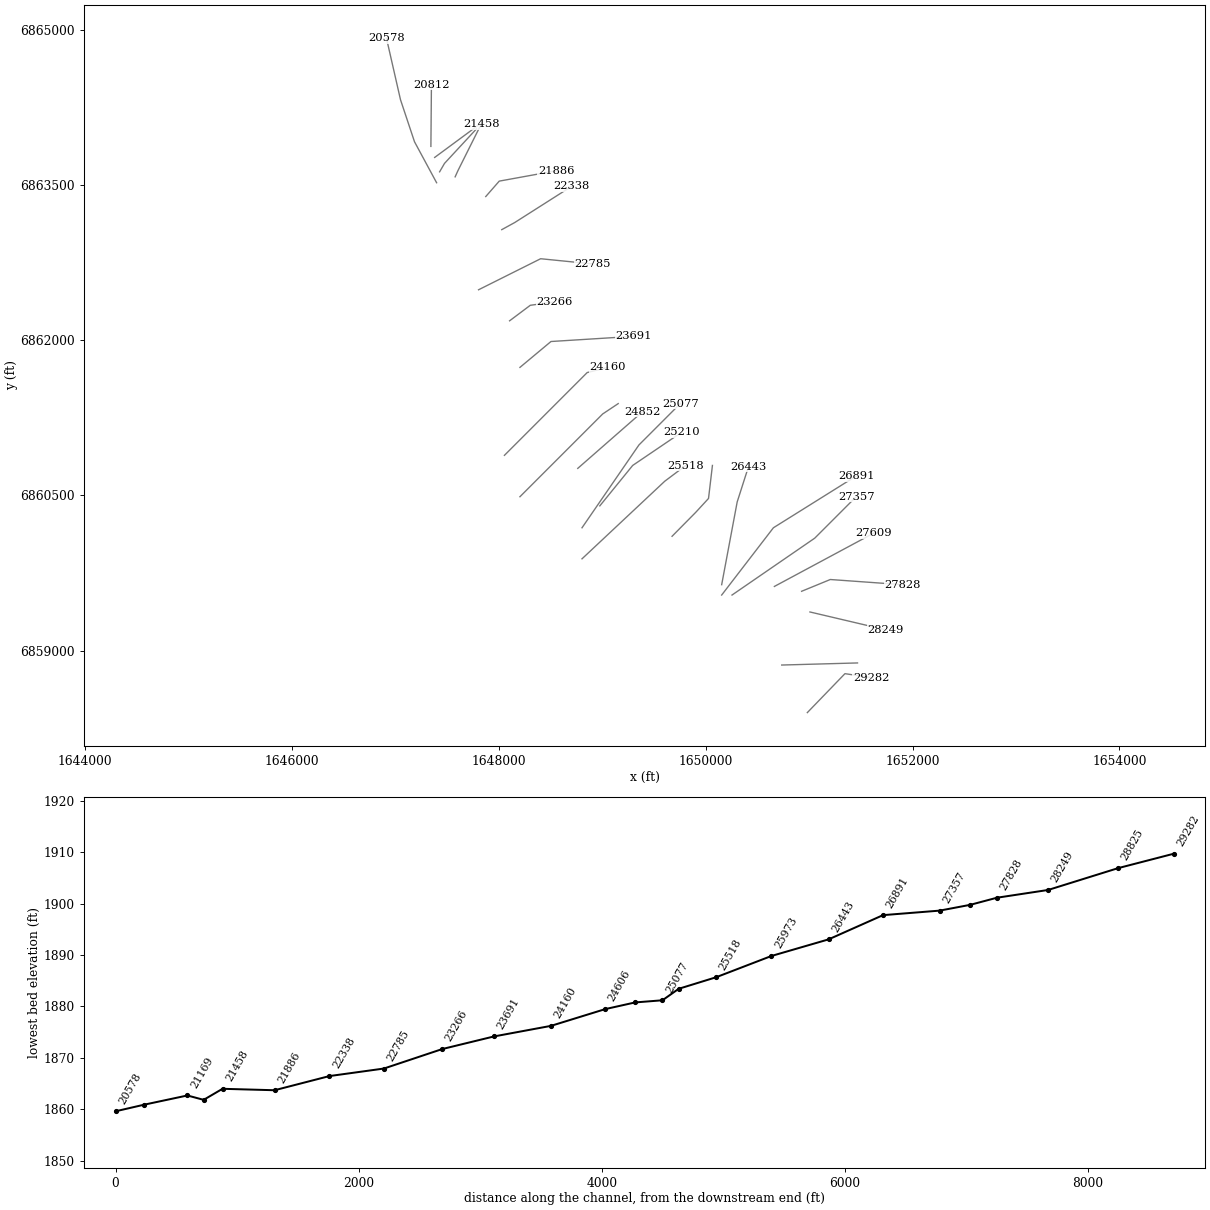
HEC-RAS study Deadman 64.prj: Deadman 64 Base Level Engineering

--- Deadman 64.g01 (geometry) --- (continued)

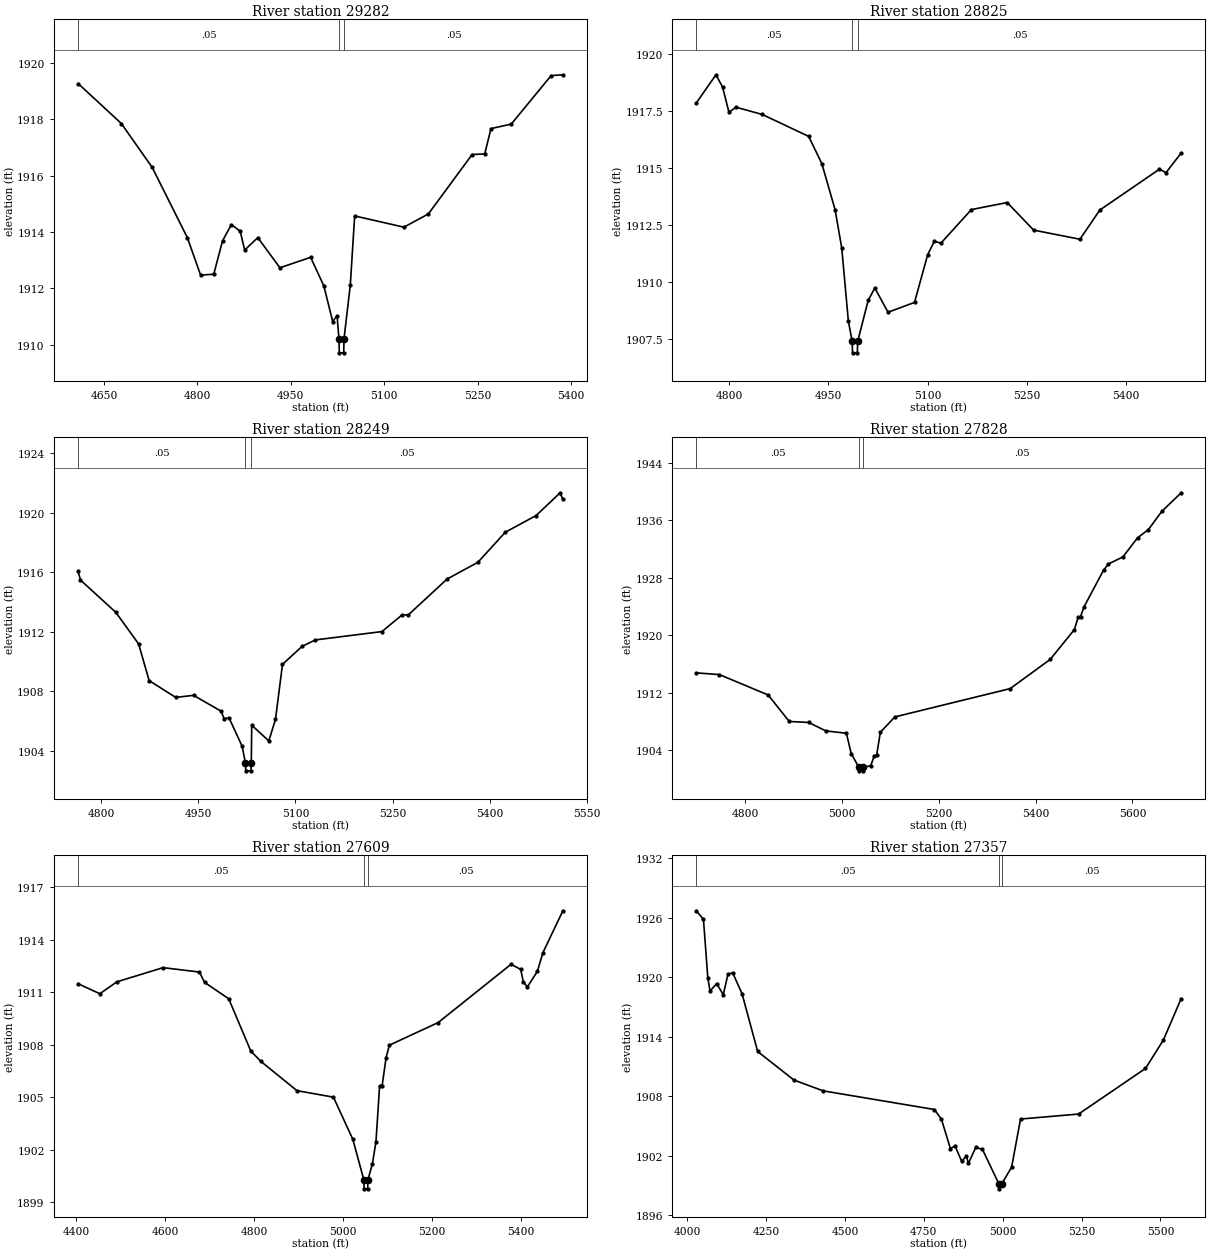
Type RM Length L Ch R = 1,29282,457,457,457
BEGIN DESCRIPTION:
Mapping XS c86eaef3
END DESCRIPTION:
XS GIS Cut Line= 3
      1650982.92      6858401.78      1651346.67      6858778.16
      1651599.22      6858740.27
#Sta/Elev= 30
  4608.2 1919.27  4677.7 1917.85  4727.3 1916.29  4783.7 1913.80  4805.0 1912.47
  4826.1 1912.50  4840.3 1913.69  4854.4 1914.26  4868.6 1914.03  4875.8 1913.36
  4896.9 1913.80  4932.4 1912.73  4981.8 1913.10  5003.1 1912.08  5017.2 1910.82
  5024.2 1911.03  5027.3 1910.21  5027.8 1909.71  5034.9 1909.71  5035.4 1910.21
  5045.5 1912.12  5052.5 1914.57  5131.6 1914.17  5170.9 1914.64  5241.2 1916.75
  5261.4 1916.77  5271.5 1917.67  5304.1 1917.83  5368.1 1919.55  5387.0 1919.58
#Mann=3,-1,0
  4608.2    0.05       0  5027.3    0.05       0  5035.4    0.05       0
Bank Sta=5027.3,5035.4
Exp/Cntr=0.3,0.1

Type RM Length L Ch R = 1,28825,576,576,576
BEGIN DESCRIPTION:
Mapping XS 68520dbd
END DESCRIPTION:
XS GIS Cut Line= 2
      1650735.41      6858861.51      1651467.93      6858881.72
#Sta/Elev= 30
  4750.3 1917.87  4779.9 1919.10  4789.9 1918.56  4799.6 1917.45  4809.9 1917.68
  4849.9 1917.36  4920.0 1916.40  4940.0 1915.20  4960.0 1913.18  4970.0 1911.51
  4980.0 1908.31  4985.8 1907.41  4986.3 1906.91  4993.6 1906.91  4994.1 1907.41
  5010.0 1909.21  5020.0 1909.75  5040.0 1908.69  5080.0 1909.12  5100.0 1911.22
  5110.0 1911.80  5120.0 1911.72  5166.0 1913.19  5220.1 1913.50  5260.1 1912.29
  5330.1 1911.89  5360.1 1913.17  5450.2 1914.96  5460.2 1914.81  5483.1 1915.67
#Mann=3,-1,0
  4750.3    0.05       0  4985.8    0.05       0  4994.1    0.05       0
Bank Sta=4985.8,4994.1
Exp/Cntr=0.3,0.1

Type RM Length L Ch R = 1,28249,421,421,421
BEGIN DESCRIPTION:
Mapping XS 9cd7c377
END DESCRIPTION:
XS GIS Cut Line= 2
      1651008.22      6859374.25      1651737.11      6859202.75
#Sta/Elev= 30
  4764.3 1916.05  4768.0 1915.47  4822.6 1913.30  4857.8 1911.18  4874.0 1908.72
  4915.1 1907.59  4942.6 1907.73  4985.0 1906.67  4990.1 1906.15  4997.3 1906.23
  5017.8 1904.30  5022.8 1903.16  5023.3 1902.66  5031.3 1902.66  5031.8 1903.16
  5032.5 1905.72  5058.9 1904.67  5069.2 1906.12  5080.0 1909.81  5110.3 1911.02
  5130.8 1911.45  5233.6 1912.01  5264.4 1913.12  5274.6 1913.14  5334.3 1915.54
  5381.8 1916.66  5424.1 1918.68  5471.7 1919.80  5508.9 1921.33  5513.1 1920.88
#Mann=3,-1,0
  4764.3    0.05       0  5022.8    0.03       0  5031.8    0.05       0
Bank Sta=5022.8,5031.8
Exp/Cntr=0.3,0.1

Type RM Length L Ch R = 1,27828,219,219,219
BEGIN DESCRIPTION:
Deadman 64 54.0
END DESCRIPTION:
XS GIS Cut Line= 3
      1650927.58      6859574.20      1651205.00      6859688.00
      1651904.96      6859638.00
#Sta/Elev= 30
  4699.2 1914.77  4746.9 1914.53  4847.7 1911.69  4891.0 1908.01  4931.0 1907.88
  4966.6 1906.70  5009.1 1906.38  5019.1 1903.55  5034.7 1901.65  5035.2 1901.15
  5043.2 1901.15  5043.7 1901.65  5059.2 1901.85  5066.7 1903.20  5071.7 1903.36
  5079.3 1906.52  5109.3 1908.65  5347.4 1912.58  5430.2 1916.64  5480.3 1920.80
  5487.8 1922.48  5492.8 1922.59  5500.3 1923.98  5540.4 1929.05  5550.5 1929.91
  5580.5 1930.90  5610.6 1933.54  5633.2 1934.70  5660.7 1937.22  5700.8 1939.81
#Mann=3,-1,0
  4699.2    0.05       0  5034.7    0.03       0  5043.7    0.05       0
Bank Sta=5034.7,5043.7
Exp/Cntr=0.3,0.1

Type RM Length L Ch R = 1,27609,252,252,252
BEGIN DESCRIPTION:
Mapping XS cce43db6
END DESCRIPTION:
XS GIS Cut Line= 2
      1650664.54      6859621.06      1651625.53      6860136.71
#Sta/Elev= 30
  4404.0 1911.49  4453.0 1910.92  4491.2 1911.60  4595.1 1912.41  4676.9 1912.16
  4688.5 1911.57  4742.9 1910.63  4792.4 1907.65  4814.4 1907.07  4896.4 1905.38
  4978.4 1905.01  5022.2 1902.59  5046.9 1900.27  5047.4 1899.77  5055.4 1899.77
  5055.9 1900.27  5066.1 1901.20  5074.1 1902.46  5082.3 1905.66  5088.0 1905.66
  5096.8 1907.26  5104.3 1907.98  5213.9 1909.27  5377.9 1912.60  5399.8 1912.31
  5405.5 1911.60  5414.6 1911.31  5437.3 1912.20  5449.4 1913.25  5494.6 1915.66
#Mann=3,-1,0
  4404.0    0.05       0  5046.9    0.05       0  5055.9    0.05       0
Bank Sta=5046.9,5055.9
Exp/Cntr=0.3,0.1

Type RM Length L Ch R = 1,27357,466,466,466
BEGIN DESCRIPTION:
Deadman 64 53.0
END DESCRIPTION:
XS GIS Cut Line= 3
      1650254.99      6859537.99      1651055.00      6860088.00
      1651454.99      6860487.99
#Sta/Elev= 30
  4029.2 1926.68  4051.6 1925.81  4065.6 1919.86  4072.5 1918.58  4093.5 1919.34
  4114.4 1918.22  4129.3 1920.28  4144.2 1920.43  4174.0 1918.31  4223.4 1912.49
  4338.4 1909.61  4431.1 1908.52  4783.5 1906.64  4805.9 1905.66  4834.3 1902.70
  4849.2 1902.95  4870.1 1901.41  4885.0 1901.96  4891.1 1901.20  4914.8 1902.82
  4935.8 1902.62  4988.0 1899.14  4988.5 1898.64  4997.2 1899.14  5028.3 1900.83
  5056.6 1905.68  5240.5 1906.18  5452.6 1910.78  5509.2 1913.64  5565.7 1917.83
#Mann=3,-1,0
  4029.2    0.05       0  4988.0    0.05       0  4997.2    0.05       0
Bank Sta=4988,4997.2
Exp/Cntr=0.3,0.1

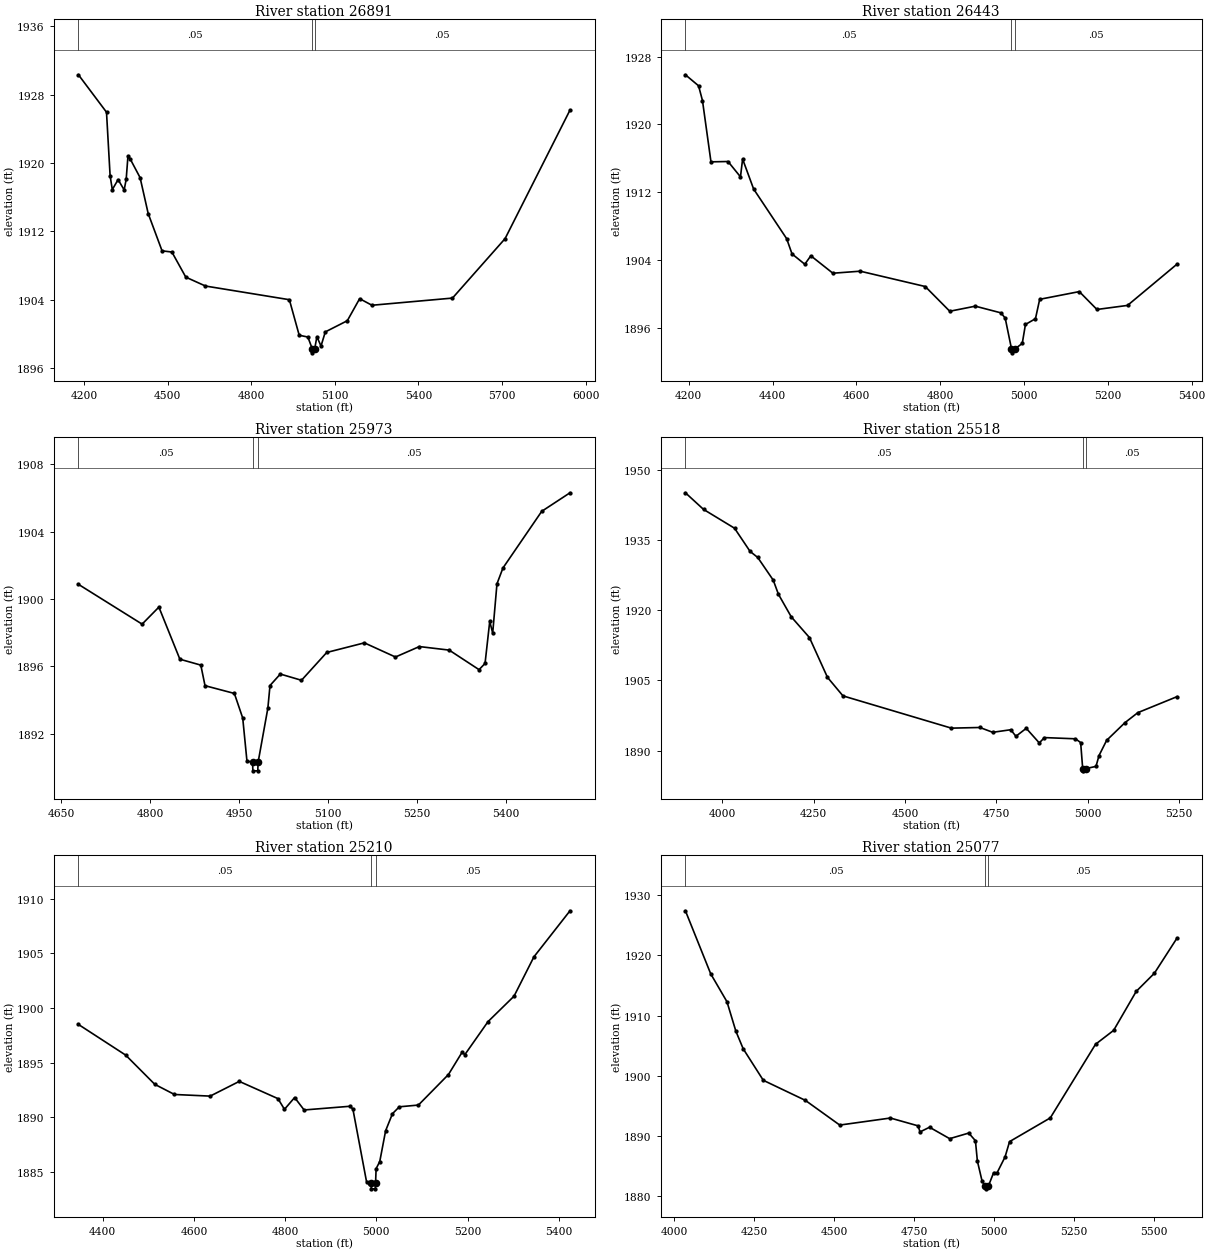
Type RM Length L Ch R = 1,26891,448,448,448
BEGIN DESCRIPTION:
Deadman 64 52.0
END DESCRIPTION:
XS GIS Cut Line= 3
      1650154.97      6859537.96      1650655.00      6860188.00
      1651454.99      6860688.00
#Sta/Elev= 30
  4180.3 1930.31  4281.0 1925.93  4293.9 1918.50  4301.8 1916.87  4322.6 1918.04
  4344.4 1916.83  4351.6 1918.07  4357.9 1920.76  4366.1 1920.45  4401.5 1918.27
  4430.5 1914.07  4480.3 1909.70  4515.6 1909.56  4565.5 1906.62  4636.1 1905.58
  4937.0 1903.98  4972.3 1899.82  5003.4 1899.61  5018.8 1898.26  5019.3 1897.76
  5028.0 1898.26  5035.8 1899.65  5050.5 1898.55  5065.9 1900.21  5144.9 1901.52
  5189.1 1904.10  5233.3 1903.33  5522.2 1904.17  5710.9 1911.13  5943.8 1926.18
#Mann=3,-1,0
  4180.3    0.05       0  5018.8    0.03       0  5028.0    0.05       0
Bank Sta=5018.8,5028
Exp/Cntr=0.3,0.1

Type RM Length L Ch R = 1,26443,470,470,470
BEGIN DESCRIPTION:
Deadman 64 51.0
END DESCRIPTION:
XS GIS Cut Line= 3
      1650155.00      6859638.00      1650305.00      6860438.00
      1650414.57      6860779.94
#Sta/Elev= 30
  4191.9 1925.87  4223.3 1924.57  4232.6 1922.83  4252.9 1915.59  4293.6 1915.63
  4323.3 1913.82  4328.4 1915.92  4354.7 1912.38  4433.5 1906.52  4446.3 1904.72
  4476.8 1903.50  4491.2 1904.50  4543.8 1902.44  4609.0 1902.68  4764.2 1900.87
  4822.7 1897.95  4883.7 1898.55  4944.8 1897.76  4955.0 1897.14  4969.9 1893.54
  4970.4 1893.04  4979.1 1893.54  4995.7 1894.15  5003.3 1896.39  5027.2 1897.07
  5037.3 1899.36  5131.8 1900.27  5173.9 1898.16  5246.9 1898.64  5364.9 1903.51
#Mann=3,-1,0
  4191.9    0.05       0  4969.9    0.05       0  4979.1    0.05       0
Bank Sta=4969.9,4979.1
Exp/Cntr=0.3,0.1

Type RM Length L Ch R = 1,25973,455,455,455
BEGIN DESCRIPTION:
Deadman 64 50.0
END DESCRIPTION:
XS GIS Cut Line= 4
      1649675.40      6860105.72      1649905.00      6860338.00
      1650027.76      6860471.31      1650065.61      6860790.35
#Sta/Elev= 30
  4678.8 1900.87  4786.2 1898.51  4814.5 1899.52  4849.9 1896.43  4885.2 1896.08
  4892.3 1894.86  4941.8 1894.40  4955.9 1892.94  4963.0 1890.40  4972.5 1890.31
  4973.0 1889.81  4981.3 1889.81  4981.8 1890.31  4998.3 1893.53  5001.9 1894.87
  5019.3 1895.55  5055.0 1895.18  5097.6 1896.83  5161.1 1897.40  5213.5 1896.56
  5253.8 1897.18  5304.1 1896.97  5354.5 1895.81  5364.6 1896.18  5372.5 1898.67
  5377.5 1897.98  5384.7 1900.90  5394.8 1901.84  5460.2 1905.20  5507.9 1906.30
#Mann=3,-1,0
  4678.8    0.05       0  4972.5    0.05       0  4981.8    0.05       0
Bank Sta=4972.5,4981.8
Exp/Cntr=0.3,0.1

Type RM Length L Ch R = 1,25518,308,308,308
BEGIN DESCRIPTION:
Deadman 64 49.0
END DESCRIPTION:
XS GIS Cut Line= 3
      1648804.98      6859887.98      1649605.00      6860638.00
      1649804.99      6860787.99
#Sta/Elev= 30
  3898.4 1945.13  3948.0 1941.58  4033.0 1937.55  4075.5 1932.60  4096.5 1931.30
  4139.0 1926.45  4153.2 1923.43  4188.3 1918.61  4238.1 1914.18  4287.5 1905.67
  4330.0 1901.70  4627.0 1894.80  4705.1 1894.94  4740.3 1893.91  4789.6 1894.46
  4803.8 1893.06  4832.1 1894.76  4867.8 1891.64  4881.9 1892.78  4966.9 1892.52
  4981.1 1891.72  4986.7 1886.17  4987.2 1885.67  4996.4 1886.17  5023.1 1886.62
  5031.5 1888.95  5052.3 1892.19  5102.3 1895.96  5137.7 1898.11  5245.0 1901.53
#Mann=3,-1,0
  3898.4    0.05       0  4986.7    0.05       0  4996.4    0.05       0
Bank Sta=4986.7,4996.4
Exp/Cntr=0.3,0.1

Type RM Length L Ch R = 1,25210,133,133,133
BEGIN DESCRIPTION:
Mapping XS b30602fd
END DESCRIPTION:
XS GIS Cut Line= 3
      1648977.05      6860399.69      1649294.78      6860790.34
      1649770.50      6861112.69
#Sta/Elev= 30
  4346.6 1898.49  4450.2 1895.68  4514.1 1893.00  4557.2 1892.07  4635.5 1891.92
  4699.4 1893.27  4784.2 1891.69  4798.5 1890.71  4820.8 1891.79  4841.6 1890.65
  4942.5 1890.99  4948.6 1890.73  4978.5 1884.08  4988.5 1883.92  4989.0 1883.42
  4997.8 1883.42  4998.3 1883.92  4999.5 1885.27  5007.5 1885.92  5020.4 1888.75
  5035.4 1890.31  5050.4 1890.94  5092.3 1891.10  5158.2 1893.90  5188.1 1895.94
  5194.1 1895.72  5245.0 1898.75  5302.0 1901.08  5345.7 1904.69  5424.8 1908.91
#Mann=3,-1,0
  4346.6    0.05       0  4988.5    0.05       0  4998.3    0.05       0
Bank Sta=4988.5,4998.3
Exp/Cntr=0.3,0.1

Type RM Length L Ch R = 1,25077,225,225,225
BEGIN DESCRIPTION:
Deadman 64 48.0
END DESCRIPTION:
XS GIS Cut Line= 3
      1648805.01      6860188.02      1649355.00      6860988.00
      1649755.01      6861388.01
#Sta/Elev= 30
  4035.3 1927.41  4114.4 1916.93  4165.2 1912.29  4193.0 1907.40  4215.9 1904.47
  4278.8 1899.23  4410.1 1895.90  4517.7 1891.79  4676.0 1892.96  4762.6 1891.66
  4768.6 1890.65  4798.4 1891.43  4861.3 1889.53  4920.9 1890.46  4941.8 1889.19
  4947.9 1885.81  4962.8 1882.43  4972.8 1881.69  4973.3 1881.19  4982.6 1881.69
  4998.7 1883.88  5009.6 1883.87  5034.4 1886.49  5048.5 1889.04  5175.8 1892.98
  5317.2 1905.22  5373.8 1907.53  5444.5 1914.02  5501.1 1917.02  5571.8 1922.86
#Mann=3,-1,0
  4035.3    0.05       0  4972.8    0.05       0  4982.6    0.05       0
Bank Sta=4972.8,4982.6
Exp/Cntr=0.3,0.1

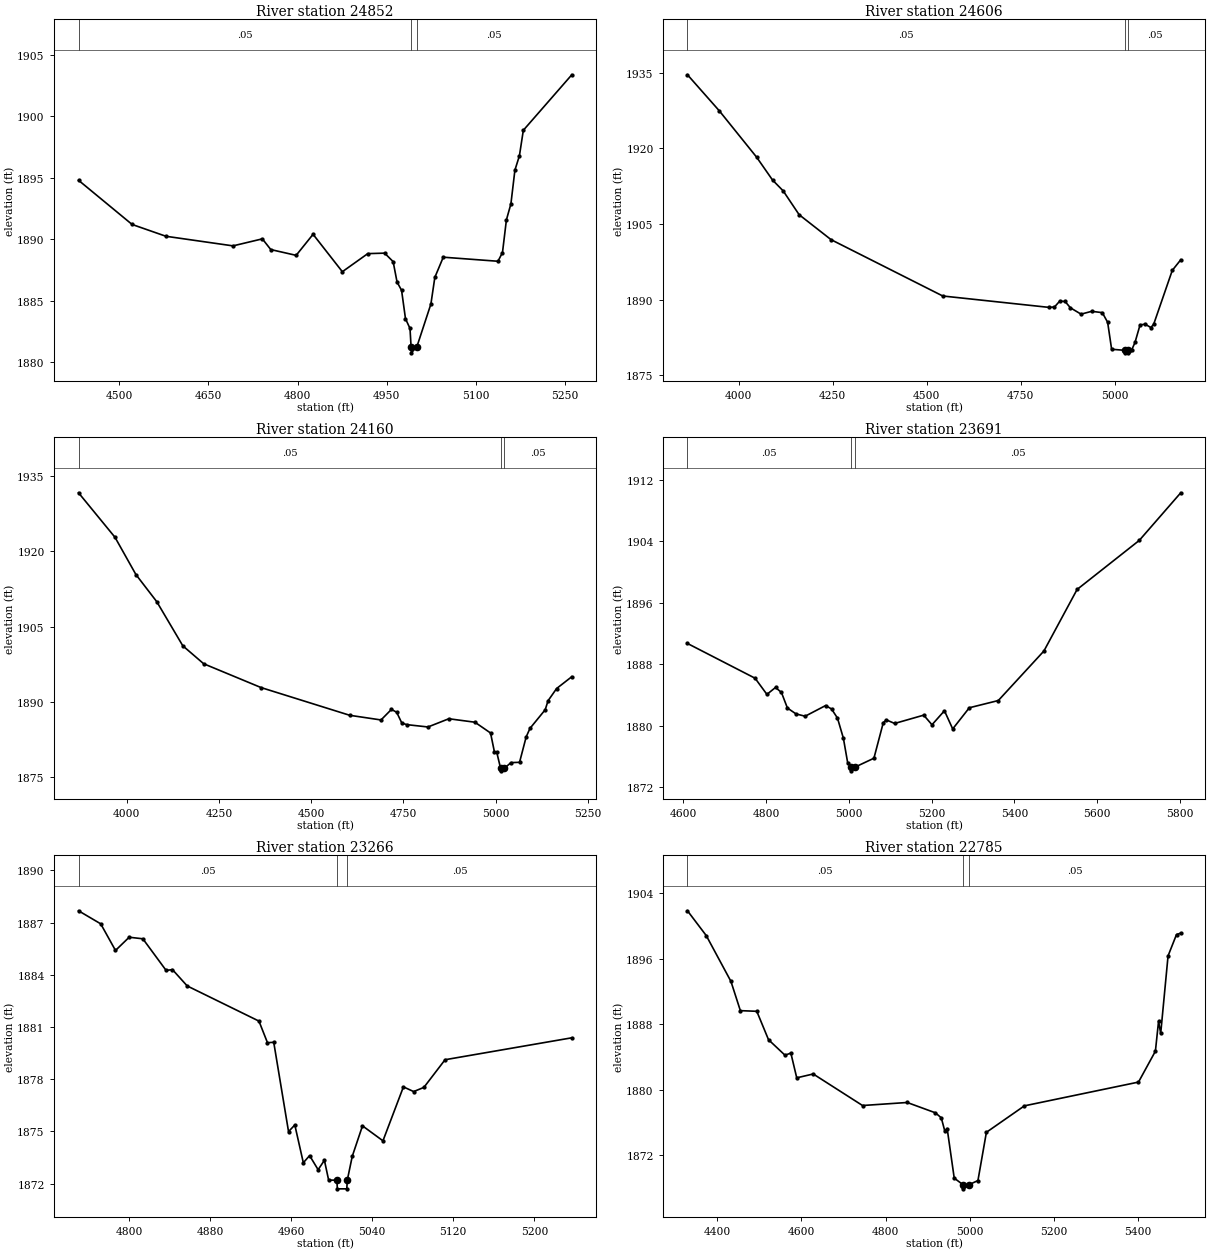
Type RM Length L Ch R = 1,24852,246,246,246
BEGIN DESCRIPTION:
Mapping XS 0c7df9de
END DESCRIPTION:
XS GIS Cut Line= 2
      1648763.95      6860761.98      1649388.96      6861308.86
#Sta/Elev= 30
  4431.2 1894.79  4521.4 1891.20  4578.4 1890.24  4691.3 1889.46  4740.7 1890.03
  4754.9 1889.16  4797.6 1888.69  4826.1 1890.40  4875.4 1887.36  4918.2 1888.83
  4946.6 1888.87  4960.9 1888.18  4967.5 1886.52  4975.1 1885.85  4981.7 1883.54
  4989.3 1882.75  4991.1 1881.27  4991.6 1880.77  5000.9 1881.27  5024.5 1884.74
  5031.1 1886.90  5045.3 1888.54  5137.4 1888.21  5145.0 1888.92  5151.6 1891.57
  5159.2 1892.88  5165.9 1895.61  5173.5 1896.78  5180.1 1898.85  5261.7 1903.36
#Mann=3,-1,0
  4431.2    0.05       0  4991.1    0.05       0  5000.9    0.05       0
Bank Sta=4991.1,5000.9
Exp/Cntr=0.3,0.1

Type RM Length L Ch R = 1,24606,446,446,446
BEGIN DESCRIPTION:
Deadman 64 47.0
END DESCRIPTION:
XS GIS Cut Line= 3
      1648205.03      6860488.03      1649005.00      6861288.00
      1649154.99      6861387.99
#Sta/Elev= 30
  3863.8 1934.60  3948.6 1927.44  4047.6 1918.27  4090.0 1913.73  4118.3 1911.58
  4160.7 1906.86  4245.6 1901.91  4542.6 1890.74  4825.4 1888.48  4839.6 1888.56
  4853.7 1889.73  4867.9 1889.65  4882.0 1888.40  4910.3 1887.14  4938.6 1887.70
  4966.8 1887.44  4981.0 1885.53  4991.6 1880.18  5026.2 1879.97  5026.7 1879.47
  5035.6 1879.47  5036.1 1879.97  5044.7 1880.00  5053.7 1881.52  5067.2 1885.01
  5080.8 1885.15  5095.8 1884.49  5103.3 1885.11  5152.9 1895.82  5175.4 1897.92
#Mann=3,-1,0
  3863.8    0.05       0  5026.2    0.05       0  5036.1    0.05       0
Bank Sta=5026.2,5036.1
Exp/Cntr=0.3,0.1

Type RM Length L Ch R = 1,24160,469,469,469
BEGIN DESCRIPTION:
Deadman 64 46.0
END DESCRIPTION:
XS GIS Cut Line= 3
      1648055.01      6860888.01      1648855.00      6861688.00
      1649054.99      6861738.00
#Sta/Elev= 30
  3869.3 1931.68  3968.3 1922.79  4024.9 1915.37  4081.4 1909.96  4152.1 1901.15
  4208.7 1897.57  4364.3 1892.82  4604.7 1887.29  4689.5 1886.36  4717.8 1888.47
  4732.0 1887.89  4746.1 1885.72  4760.2 1885.42  4816.8 1884.96  4873.4 1886.60
  4944.1 1885.91  4986.5 1883.76  4997.1 1879.95  5003.2 1879.95  5013.7 1876.71
  5014.2 1876.21  5023.7 1876.71  5041.9 1877.85  5065.1 1877.91  5083.1 1882.98
  5093.4 1884.68  5134.7 1888.40  5142.4 1890.19  5165.6 1892.63  5206.8 1894.99
#Mann=3,-1,0
  3869.3    0.05       0  5013.7    0.05       0  5023.7    0.05       0
Bank Sta=5013.7,5023.7
Exp/Cntr=0.3,0.1

Type RM Length L Ch R = 1,23691,425,425,425
BEGIN DESCRIPTION:
Deadman 64 45.0
END DESCRIPTION:
XS GIS Cut Line= 3
      1648205.01      6861738.01      1648505.00      6861988.00
      1649305.04      6862038.00
#Sta/Elev= 30
  4609.7 1890.71  4773.1 1886.19  4801.7 1884.09  4822.5 1884.99  4836.8 1884.34
  4851.2 1882.32  4872.0 1881.55  4894.1 1881.25  4943.6 1882.64  4957.9 1882.19
  4972.2 1881.01  4986.5 1878.39  4996.9 1875.19  5005.2 1874.65  5005.7 1874.15
  5015.2 1874.65  5060.3 1875.79  5082.9 1880.41  5090.4 1880.77  5110.4 1880.31
  5180.6 1881.39  5200.6 1880.14  5230.7 1881.96  5250.7 1879.60  5290.8 1882.35
  5360.9 1883.29  5471.1 1889.73  5551.3 1897.73  5701.6 1904.11  5801.8 1910.30
#Mann=3,-1,0
  4609.7    0.05       0  5005.2    0.05       0  5015.2    0.05       0
Bank Sta=5005.2,5015.2
Exp/Cntr=0.3,0.1

Type RM Length L Ch R = 1,23266,481,481,481
BEGIN DESCRIPTION:
Deadman 64 44.0
END DESCRIPTION:
XS GIS Cut Line= 3
      1648105.00      6862188.00      1648305.00      6862338.00
      1648539.58      6862371.07
#Sta/Elev= 30
  4750.1 1887.68  4772.0 1886.93  4786.6 1885.40  4800.1 1886.16  4813.6 1886.07
  4836.6 1884.25  4842.8 1884.30  4857.4 1883.36  4928.2 1881.34  4936.6 1880.10
  4942.8 1880.12  4957.4 1874.99  4963.6 1875.37  4972.0 1873.20  4978.2 1873.61
  4986.6 1872.80  4992.8 1873.34  4997.0 1872.20  5005.1 1872.20  5005.6 1871.70
  5014.9 1871.70  5015.4 1872.20  5020.3 1873.57  5030.4 1875.32  5050.6 1874.46
  5070.8 1877.56  5080.9 1877.29  5091.0 1877.53  5111.9 1879.12  5237.0 1880.38
#Mann=3,-1,0
  4750.1    0.05       0  5005.1    0.05       0  5015.4    0.05       0
Bank Sta=5005.1,5015.4
Exp/Cntr=0.3,0.1

Type RM Length L Ch R = 1,22785,447,447,447
BEGIN DESCRIPTION:
Deadman 64 43.0
END DESCRIPTION:
XS GIS Cut Line= 3
      1647805.02      6862488.01      1648405.00      6862788.00
      1648905.01      6862738.00
#Sta/Elev= 30
  4328.9 1901.84  4373.6 1898.81  4432.3 1893.22  4454.7 1889.65  4493.8 1889.57
  4521.7 1886.10  4560.9 1884.21  4574.8 1884.47  4588.8 1881.45  4628.0 1881.92
  4745.3 1878.07  4851.6 1878.44  4918.6 1877.18  4932.6 1876.57  4941.0 1874.95
  4946.6 1875.26  4963.4 1869.21  4984.4 1868.40  4984.9 1867.90  4998.2 1868.40
  5019.8 1868.91  5039.9 1874.80  5130.3 1878.03  5401.7 1880.93  5441.9 1884.70
  5449.4 1888.35  5454.5 1886.87  5472.0 1896.33  5492.1 1898.94  5502.2 1899.11
#Mann=3,-1,0
  4328.9    0.05       0  4984.4    0.05       0  4998.2    0.05       0
Bank Sta=4984.4,4998.2
Exp/Cntr=0.3,0.1

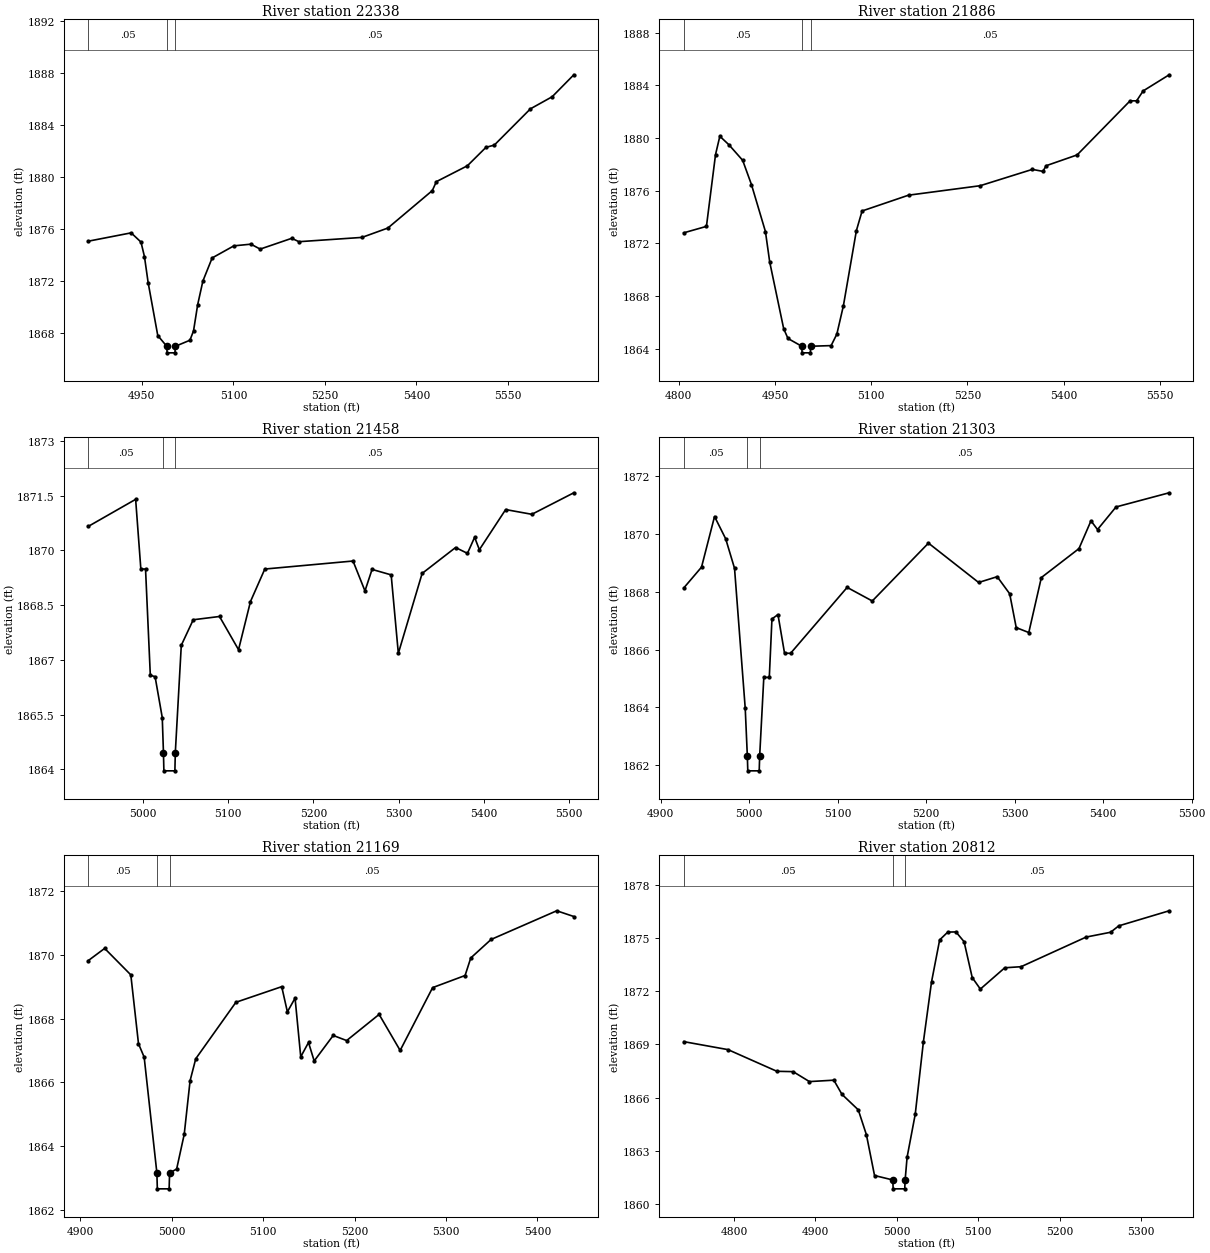
Type RM Length L Ch R = 1,22338,452,452,452
BEGIN DESCRIPTION:
Deadman 64 42.0
END DESCRIPTION:
XS GIS Cut Line= 3
      1648029.15      6863068.99      1648155.00      6863138.00
      1648704.96      6863487.97
#Sta/Elev= 30
  4862.4 1875.03  4932.5 1875.67  4948.6 1874.96  4954.3 1873.84  4960.3 1871.85
  4976.1 1867.77  4990.9 1866.94  4991.4 1866.44  5004.3 1866.44  5004.8 1866.94
  5028.8 1867.41  5034.7 1868.13  5041.5 1870.15  5050.0 1871.96  5065.2 1873.74
  5100.8 1874.67  5128.7 1874.80  5143.9 1874.42  5195.6 1875.25  5207.4 1874.99
  5310.7 1875.32  5353.1 1876.04  5425.9 1878.92  5432.6 1879.61  5483.4 1880.83
  5513.9 1882.25  5527.5 1882.42  5586.7 1885.21  5622.3 1886.14  5657.8 1887.83
#Mann=3,-1,0
  4862.4    0.05       0  4990.9    0.05       0  5004.8    0.05       0
Bank Sta=4990.9,5004.8
Exp/Cntr=0.3,0.1

Type RM Length L Ch R = 1,21886,428,428,428
BEGIN DESCRIPTION:
Deadman 64 41.0
END DESCRIPTION:
XS GIS Cut Line= 3
      1647874.51      6863388.87      1648005.00      6863538.00
      1648555.03      6863638.01
#Sta/Elev= 30
  4807.6 1872.80  4843.0 1873.29  4857.2 1878.75  4863.9 1880.14  4878.1 1879.49
  4899.5 1878.31  4913.2 1876.47  4935.0 1872.90  4941.7 1870.58  4963.5 1865.51
  4970.2 1864.77  4991.7 1864.18  4992.2 1863.68  5005.1 1863.68  5005.6 1864.18
  5037.5 1864.23  5046.4 1865.10  5056.6 1867.25  5076.9 1872.97  5085.8 1874.46
  5158.2 1875.66  5270.0 1876.38  5351.3 1877.62  5367.8 1877.47  5372.9 1877.90
  5421.2 1878.72  5503.8 1882.83  5514.0 1882.83  5524.1 1883.58  5564.8 1884.81
#Mann=3,-1,0
  4807.6    0.05       0  4991.7    0.05       0  5005.6    0.05       0
Bank Sta=4991.7,5005.6
Exp/Cntr=0.3,0.1

Type RM Length L Ch R = 1,21458,155,155,155
BEGIN DESCRIPTION:
Deadman 64 40.0
END DESCRIPTION:
XS GIS Cut Line= 3
      1647578.65      6863579.44      1647605.00      6863638.00
      1647830.75      6864089.49
#Sta/Elev= 30
  4936.3 1870.66  4991.7 1871.40  4997.8 1869.49  5003.3 1869.49  5008.9 1866.58
  5014.5 1866.54  5022.9 1865.42  5024.3 1864.46  5024.8 1863.96  5037.7 1863.96
  5038.2 1864.46  5045.2 1867.40  5059.2 1868.10  5090.0 1868.19  5112.3 1867.28
  5126.3 1868.60  5143.1 1869.49  5246.5 1869.71  5260.5 1868.89  5268.8 1869.48
  5291.2 1869.33  5299.6 1867.18  5327.5 1869.37  5366.7 1870.08  5380.6 1869.92
  5389.0 1870.36  5394.6 1870.02  5425.4 1871.12  5456.1 1870.99  5505.3 1871.58
#Mann=3,-1,0
  4936.3    0.05       0  5024.3    0.03       0  5038.2    0.05       0
Bank Sta=5024.3,5038.2
Exp/Cntr=0.3,0.1

Type RM Length L Ch R = 1,21303,134,134,134
BEGIN DESCRIPTION:
Mapping XS 1d7341ee
END DESCRIPTION:
XS GIS Cut Line= 3
      1647428.54      6863627.94      1647475.90      6863709.40
      1647784.71      6864042.84
#Sta/Elev= 30
  4925.9 1868.13  4946.0 1868.85  4960.7 1870.60  4973.3 1869.83  4983.3 1868.81
  4995.4 1863.97  4997.8 1862.31  4998.3 1861.81  5011.2 1861.81  5011.7 1862.31
  5016.4 1865.04  5022.6 1865.04  5025.6 1867.06  5032.4 1867.21  5039.8 1865.88
  5046.6 1865.87  5110.6 1868.15  5139.0 1867.68  5202.5 1869.68  5259.2 1868.32
  5280.2 1868.52  5294.3 1867.93  5301.7 1866.76  5315.9 1866.59  5330.1 1868.49
  5372.6 1869.49  5386.2 1870.45  5393.6 1870.15  5414.5 1870.93  5474.6 1871.42
#Mann=3,-1,0
  4925.9    0.05       0  4997.8    0.03       0  5011.7    0.05       0
Bank Sta=4997.8,5011.7
Exp/Cntr=0.3,0.1

Type RM Length L Ch R = 1,21169,357,357,357
BEGIN DESCRIPTION:
Mapping XS 367cddb1
END DESCRIPTION:
XS GIS Cut Line= 2
      1647380.70      6863766.90      1647807.83      6864082.03
#Sta/Elev= 30
  4909.0 1869.82  4926.8 1870.20  4955.4 1869.37  4963.8 1867.21  4970.0 1866.79
  4983.9 1863.16  4984.4 1862.66  4997.3 1862.66  4997.8 1863.16  5005.5 1863.28
  5013.8 1864.37  5020.2 1866.05  5026.4 1866.74  5070.3 1868.51  5120.4 1869.00
  5126.6 1868.21  5135.0 1868.64  5141.2 1866.80  5149.7 1867.25  5155.9 1866.67
  5176.7 1867.47  5191.4 1867.31  5226.9 1868.13  5249.9 1867.00  5285.4 1868.97
  5320.9 1869.35  5327.1 1869.90  5349.3 1870.48  5421.1 1871.38  5439.8 1871.20
#Mann=3,-1,0
  4909.0    0.05       0  4983.9    0.03       0  4997.8    0.05       0
Bank Sta=4983.9,4997.8
Exp/Cntr=0.3,0.1

Type RM Length L Ch R = 1,20812,234,234,234
BEGIN DESCRIPTION:
Mapping XS f0591220
END DESCRIPTION:
XS GIS Cut Line= 2
      1647344.26      6863873.63      1647349.46      6864470.01
#Sta/Elev= 30
  4738.2 1869.15  4792.6 1868.70  4852.6 1867.48  4872.6 1867.46  4892.6 1866.90
  4922.6 1866.98  4932.6 1866.18  4952.6 1865.31  4962.6 1863.91  4972.6 1861.61
  4995.0 1861.36  4995.5 1860.86  5009.7 1860.86  5010.2 1861.36  5012.6 1862.64
  5022.6 1865.06  5032.6 1869.13  5042.6 1872.51  5052.6 1874.88  5062.6 1875.32
  5072.6 1875.33  5082.6 1874.78  5092.6 1872.76  5102.6 1872.11  5132.6 1873.31
  5152.6 1873.37  5232.6 1875.04  5262.6 1875.31  5272.6 1875.67  5334.6 1876.52
#Mann=3,-1,0
  4738.2    0.05       0  4995.0    0.05       0  5010.2    0.05       0
Bank Sta=4995,5010.2
Exp/Cntr=0.3,0.1

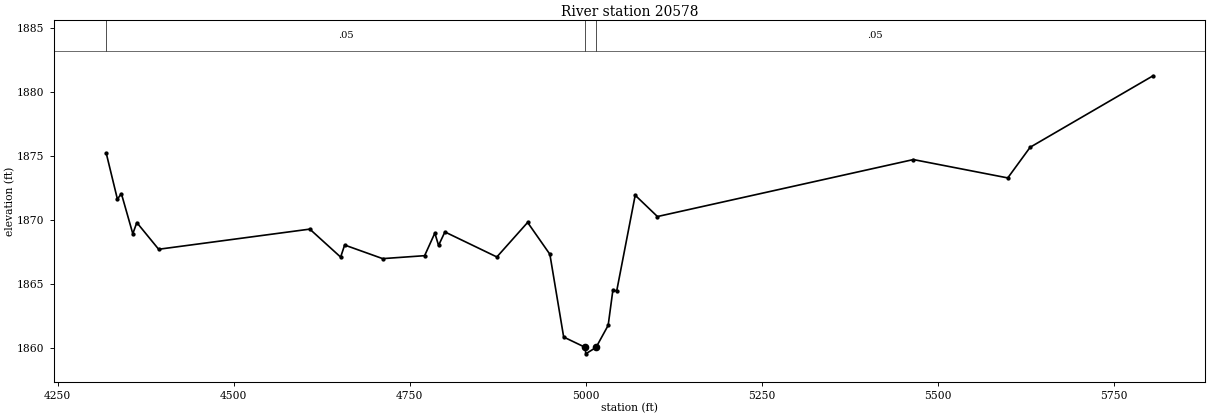
Type RM Length L Ch R = 1,20578,182,182,182
BEGIN DESCRIPTION:
Mapping XS 2231ef33
END DESCRIPTION:
XS GIS Cut Line= 4
      1647399.41      6863522.39      1647185.85      6863918.25
      1647050.44      6864324.50      1646915.02      6864918.24
#Sta/Elev= 30
  4319.1 1875.23  4335.0 1871.64  4340.7 1872.06  4356.9 1868.94  4362.6 1869.81
  4393.6 1867.73  4608.3 1869.30  4652.1 1867.12  4657.8 1868.06  4711.8 1867.00
  4771.4 1867.23  4785.9 1868.99  4791.2 1868.03  4800.2 1869.08  4874.0 1867.13
  4917.7 1869.82  4949.3 1867.34  4968.9 1860.89  4999.7 1860.08  5000.2 1859.58
  5014.9 1860.08  5032.1 1861.80  5038.9 1864.58  5044.2 1864.47  5070.5 1871.94
  5102.1 1870.28  5465.6 1874.72  5599.7 1873.29  5631.5 1875.68  5806.1 1881.25
#Mann=3,-1,0
  4319.1    0.05       0  4999.7    0.05       0  5014.9    0.05       0
Bank Sta=4999.7,5014.9
Exp/Cntr=0.3,0.1