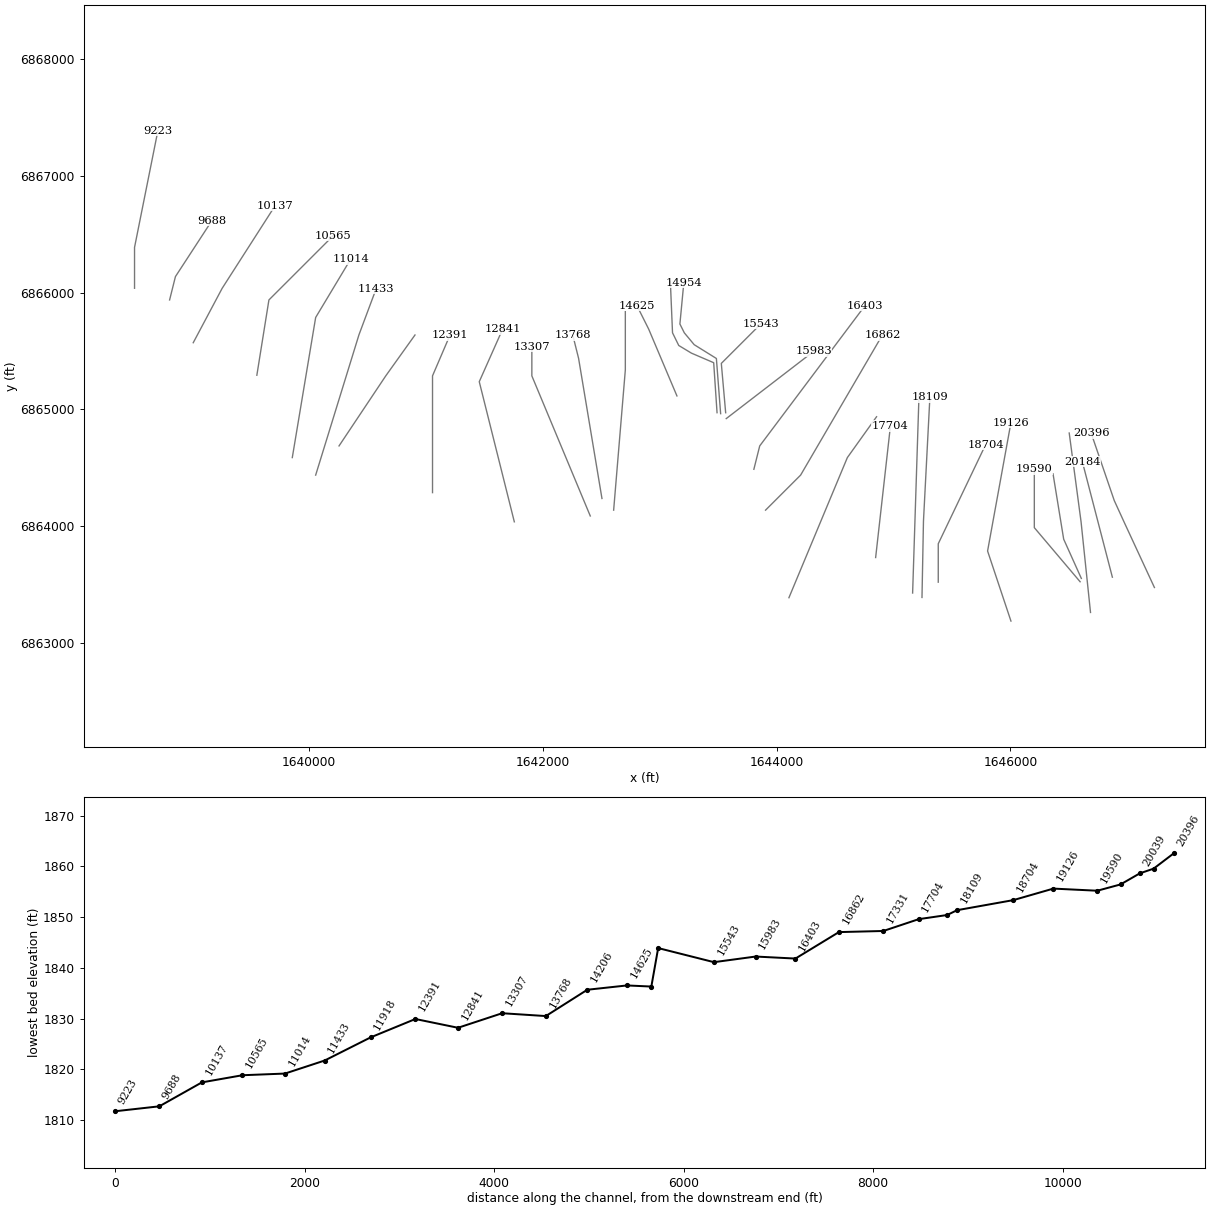
HEC-RAS study Deadman 64.prj: Deadman 64 Base Level Engineering

--- Deadman 64.g01 (geometry) --- (continued)

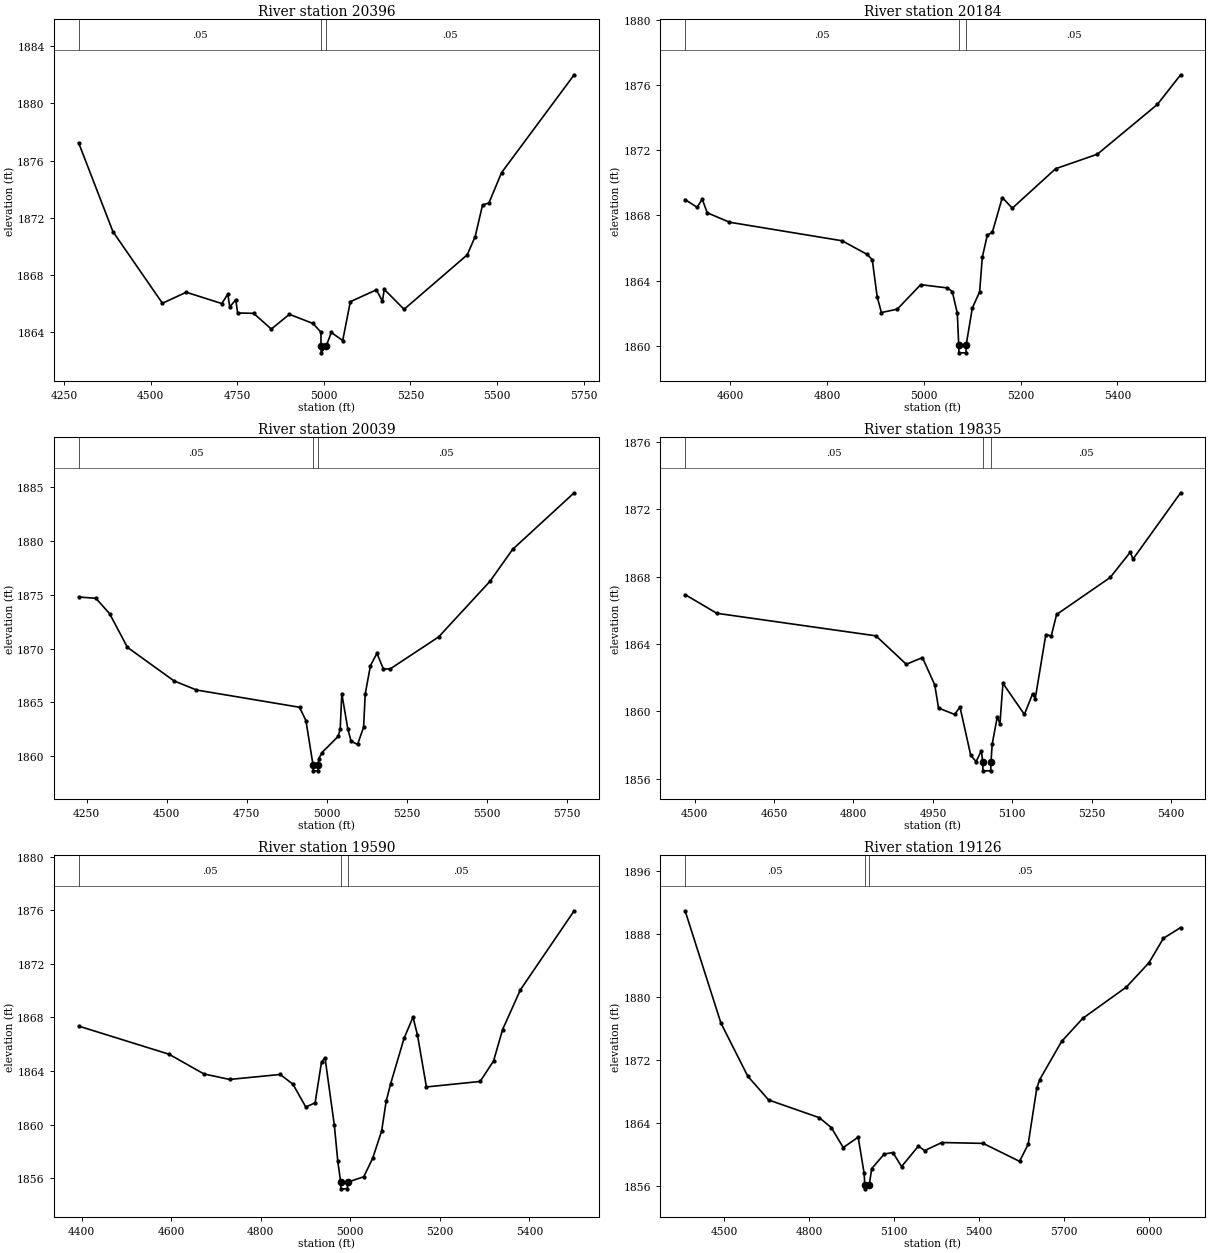
Type RM Length L Ch R = 1,20396,212,212,212
BEGIN DESCRIPTION:
Mapping XS 50611a39
END DESCRIPTION:
XS GIS Cut Line= 4
      1647232.75      6863475.51      1646972.31      6864038.05
      1646888.98      6864220.34      1646691.06      6864798.46
#Sta/Elev= 30
  4291.5 1877.24  4390.6 1871.04  4533.6 1866.04  4602.4 1866.81  4705.1 1866.02
  4722.5 1866.68  4728.0 1865.79  4745.4 1866.28  4750.9 1865.36  4796.8 1865.34
  4848.1 1864.24  4900.3 1865.27  4968.4 1864.63  4991.5 1864.02  4991.6 1863.08
  4992.1 1862.58  5007.1 1863.08  5021.3 1864.00  5054.3 1863.44  5076.3 1866.15
  5151.6 1866.98  5169.0 1866.19  5174.3 1867.01  5231.6 1865.62  5414.0 1869.42
  5437.0 1870.70  5458.2 1872.90  5476.6 1873.04  5513.2 1875.16  5722.9 1881.99
#Mann=3,-1,0
  4291.5    0.05       0  4991.6    0.03       0  5007.1    0.05       0
Bank Sta=4991.6,5007.1
Exp/Cntr=0.3,0.1

Type RM Length L Ch R = 1,20184,145,145,145
BEGIN DESCRIPTION:
Mapping XS 25d5ae7a
END DESCRIPTION:
XS GIS Cut Line= 2
      1646872.89      6863563.81      1646615.47      6864554.51
#Sta/Elev= 30
  4506.9 1868.97  4531.9 1868.49  4542.2 1869.00  4552.6 1868.16  4598.5 1867.58
  4831.4 1866.44  4883.2 1865.60  4893.5 1865.28  4903.8 1862.98  4912.5 1862.04
  4945.2 1862.25  4993.6 1863.75  5048.5 1863.55  5058.8 1863.33  5069.2 1861.99
  5072.1 1860.07  5072.6 1859.57  5087.1 1859.57  5087.6 1860.07  5100.2 1862.32
  5115.3 1863.31  5120.8 1865.43  5131.2 1866.79  5141.5 1866.96  5162.1 1869.09
  5182.8 1868.44  5272.3 1870.86  5358.5 1871.75  5482.4 1874.80  5530.5 1876.62
#Mann=3,-1,0
  4506.9    0.05       0  5072.1    0.05       0  5087.6    0.05       0
Bank Sta=5072.1,5087.6
Exp/Cntr=0.3,0.1

Type RM Length L Ch R = 1,20039,204,204,204
BEGIN DESCRIPTION:
Deadman 64 38.0
END DESCRIPTION:
XS GIS Cut Line= 3
      1646685.85      6863262.00      1646605.00      6864038.00
      1646503.56      6864798.47
#Sta/Elev= 30
  4225.1 1874.78  4279.0 1874.66  4321.6 1873.24  4377.5 1870.11  4522.7 1867.00
  4593.1 1866.15  4914.8 1864.55  4934.9 1863.31  4957.3 1859.15  4957.8 1858.65
  4972.4 1858.65  4972.9 1859.15  4975.1 1859.77  4985.2 1860.35  5035.6 1861.85
  5041.9 1862.53  5046.9 1865.82  5065.8 1862.51  5075.9 1861.40  5096.1 1861.10
  5115.0 1862.71  5120.0 1865.78  5136.4 1868.42  5156.6 1869.55  5176.8 1868.10
  5198.2 1868.11  5349.5 1871.08  5509.7 1876.24  5580.3 1879.20  5772.5 1884.45
#Mann=3,-1,0
  4225.1    0.05       0  4957.3    0.05       0  4972.9    0.05       0
Bank Sta=4957.3,4972.9
Exp/Cntr=0.3,0.1

Type RM Length L Ch R = 1,19835,245,245,245
BEGIN DESCRIPTION:
Mapping XS b94d3df6
END DESCRIPTION:
XS GIS Cut Line= 3
      1646607.29      6863553.34      1646456.24      6863889.30
      1646365.09      6864449.17
#Sta/Elev= 30
  4482.1 1866.93  4542.0 1865.82  4842.4 1864.48  4899.8 1862.79  4930.2 1863.19
  4953.5 1861.56  4960.6 1860.19  4991.0 1859.81  5001.1 1860.25  5021.4 1857.38
  5031.5 1857.01  5041.6 1857.66  5044.0 1856.96  5044.5 1856.46  5059.1 1856.46
  5059.6 1856.96  5061.9 1858.04  5071.5 1859.67  5076.5 1859.25  5082.2 1861.66
  5122.7 1859.81  5138.1 1861.03  5143.1 1860.74  5163.2 1864.56  5173.4 1864.47
  5183.5 1865.75  5284.8 1867.95  5322.6 1869.45  5327.7 1869.04  5417.7 1872.98
#Mann=3,-1,0
  4482.1    0.05       0  5044.0    0.05       0  5059.6    0.05       0
Bank Sta=5044,5059.6
Exp/Cntr=0.3,0.1

Type RM Length L Ch R = 1,19590,464,464,464
BEGIN DESCRIPTION:
Deadman 64 37.0
END DESCRIPTION:
XS GIS Cut Line= 3
      1646596.89      6863524.69      1646205.00      6863988.00
      1646205.00      6864487.98
#Sta/Elev= 30
  4393.3 1867.36  4595.2 1865.26  4673.2 1863.79  4730.4 1863.38  4843.5 1863.75
  4872.1 1863.02  4900.7 1861.32  4921.5 1861.64  4935.8 1864.68  4943.6 1865.00
  4964.4 1859.97  4972.1 1857.29  4978.6 1855.72  4979.1 1855.22  4993.7 1855.22
  4994.2 1855.72  5030.1 1856.12  5050.1 1857.50  5070.1 1859.54  5080.1 1861.74
  5090.1 1863.05  5120.1 1866.44  5140.1 1868.03  5150.1 1866.69  5170.1 1862.82
  5290.1 1863.23  5320.1 1864.76  5340.1 1867.09  5380.1 1870.07  5500.1 1875.96
#Mann=3,-1,0
  4393.3    0.05       0  4978.6    0.03       0  4994.2    0.05       0
Bank Sta=4978.6,4994.2
Exp/Cntr=0.3,0.1

Type RM Length L Ch R = 1,19126,422,422,422
BEGIN DESCRIPTION:
Deadman 64 36.0
END DESCRIPTION:
XS GIS Cut Line= 3
      1646005.01      6863187.96      1645805.00      6863788.00
      1646004.99      6864887.97
#Sta/Elev= 30
  4362.1 1890.94  4488.6 1876.69  4583.5 1869.94  4657.3 1866.92  4836.5 1864.67
  4878.7 1863.41  4920.8 1860.88  4973.5 1862.20  4994.6 1857.59  4996.8 1856.14
  4997.3 1855.64  5012.7 1856.14  5021.3 1858.21  5065.7 1860.06  5096.2 1860.25
  5126.7 1858.47  5186.4 1861.07  5208.0 1860.49  5269.0 1861.52  5415.1 1861.41
  5543.5 1859.13  5573.9 1861.29  5604.4 1868.40  5614.6 1869.50  5692.1 1874.35
  5767.1 1877.29  5920.8 1881.25  6000.8 1884.35  6051.7 1887.44  6112.6 1888.81
#Mann=3,-1,0
  4362.1    0.05       0  4996.8    0.03       0  5012.7    0.05       0
Bank Sta=4996.8,5012.7
Exp/Cntr=0.3,0.1

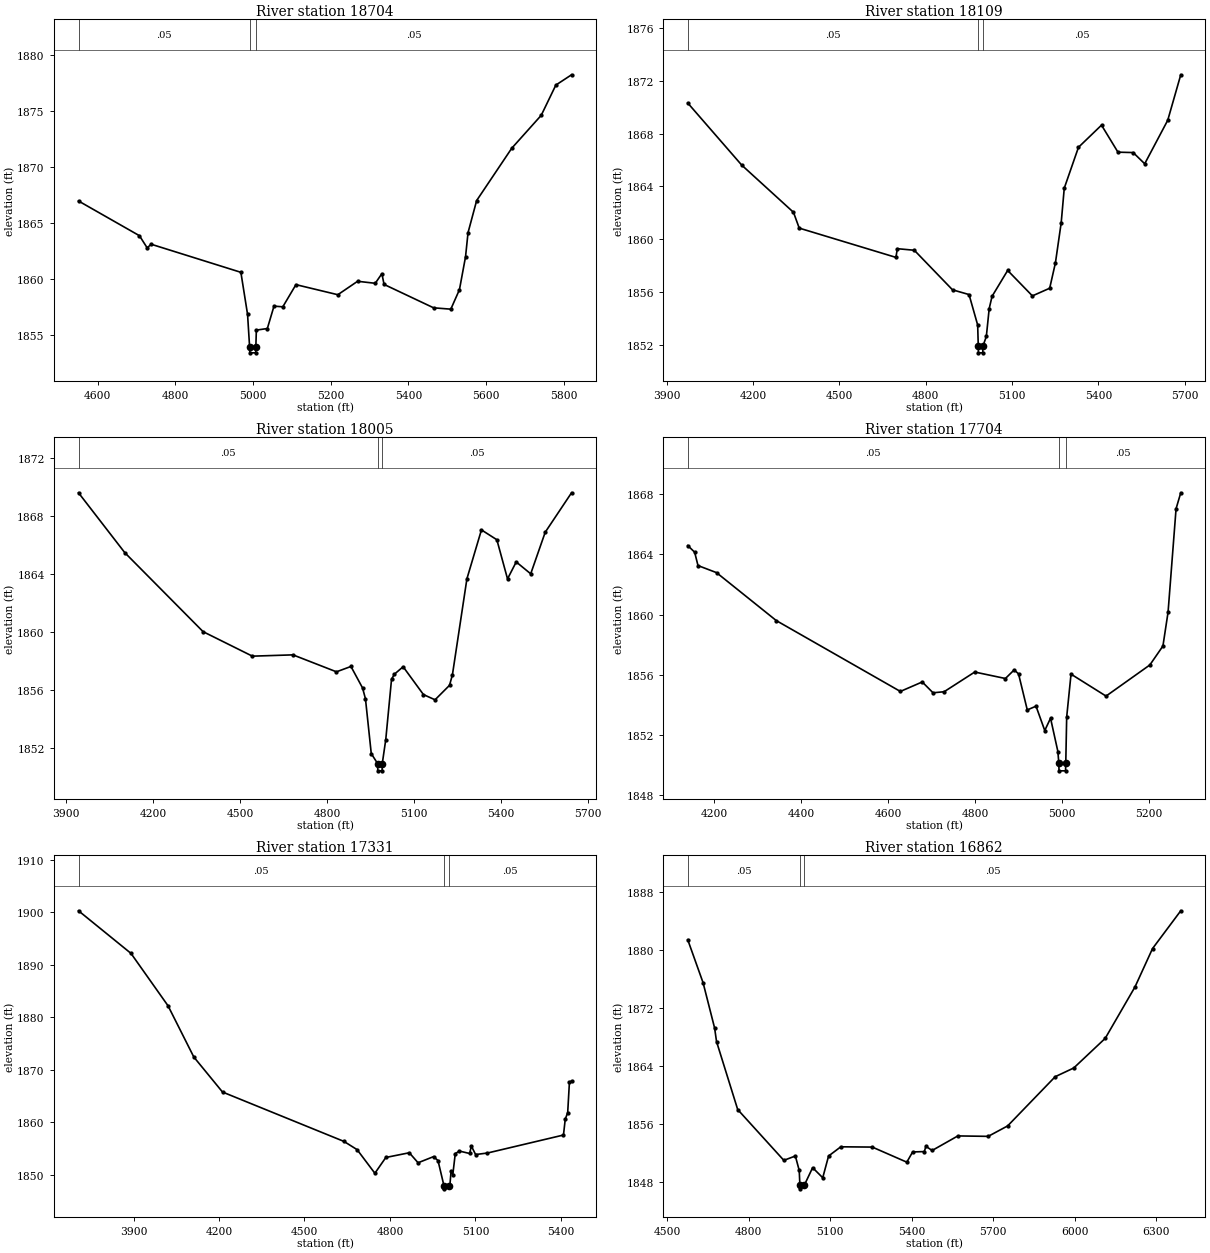
Type RM Length L Ch R = 1,18704,595,595,595
BEGIN DESCRIPTION:
Mapping XS cdbbc454
END DESCRIPTION:
XS GIS Cut Line= 3
      1645382.92      6863521.22      1645382.92      6863850.28
      1645787.97      6864698.35
#Sta/Elev= 30
  4551.0 1866.93  4707.8 1863.83  4727.8 1862.74  4737.8 1863.07  4968.9 1860.56
  4986.1 1856.80  4991.4 1853.87  4991.9 1853.37  5006.9 1853.37  5007.4 1853.87
  5008.7 1855.40  5037.0 1855.54  5054.1 1857.54  5076.8 1857.48  5110.6 1859.46
  5218.4 1858.56  5269.3 1859.76  5314.7 1859.58  5331.8 1860.44  5337.4 1859.48
  5464.9 1857.39  5509.2 1857.27  5531.4 1859.01  5547.1 1861.95  5553.5 1864.10
  5575.7 1866.97  5666.0 1871.64  5741.9 1874.58  5779.5 1877.28  5819.9 1878.20
#Mann=3,-1,0
  4551.0    0.05       0  4991.4    0.03       0  5007.4    0.05       0
Bank Sta=4991.4,5007.4
Exp/Cntr=0.3,0.1

Type RM Length L Ch R = 1,18109,104,104,104
BEGIN DESCRIPTION:
Mapping XS 8bef14d4
END DESCRIPTION:
XS GIS Cut Line= 3
      1645243.68      6863390.35      1645256.34      6864044.37
      1645311.18      6865103.21
#Sta/Elev= 30
  3972.3 1870.33  4160.0 1865.62  4340.0 1862.04  4360.0 1860.84  4696.2 1858.62
  4701.2 1859.28  4760.2 1859.16  4893.0 1856.16  4950.5 1855.80  4980.5 1853.49
  4982.6 1851.88  4983.1 1851.38  4998.1 1851.38  4998.6 1851.88  5010.6 1852.62
  5020.6 1854.74  5030.6 1855.67  5084.8 1857.63  5170.8 1855.70  5230.9 1856.28
  5250.9 1858.21  5270.9 1861.24  5281.6 1863.87  5331.0 1866.97  5411.1 1868.65
  5468.3 1866.60  5521.3 1866.57  5561.3 1865.72  5641.4 1869.02  5686.7 1872.47
#Mann=3,-1,0
  3972.3    0.05       0  4982.6    0.05       0  4998.6    0.05       0
Bank Sta=4982.6,4998.6
Exp/Cntr=0.3,0.1

Type RM Length L Ch R = 1,18005,301,301,301
BEGIN DESCRIPTION:
Mapping XS e1e030d0
END DESCRIPTION:
XS GIS Cut Line= 2
      1645163.52      6863428.36      1645218.37      6865128.78
#Sta/Elev= 30
  3942.1 1869.61  4101.8 1865.48  4372.0 1860.03  4542.1 1858.34  4682.1 1858.43
  4832.2 1857.26  4882.2 1857.63  4922.2 1856.15  4932.3 1855.40  4952.3 1851.62
  4974.3 1850.93  4974.8 1850.43  4989.8 1850.43  4990.3 1850.93  5002.3 1852.58
  5022.3 1856.75  5032.3 1857.10  5062.3 1857.61  5132.4 1855.69  5172.4 1855.33
  5222.4 1856.33  5232.4 1857.06  5282.4 1863.68  5332.5 1867.05  5385.7 1866.37
  5422.5 1863.67  5452.5 1864.84  5502.5 1864.02  5552.6 1866.89  5643.4 1869.61
#Mann=3,-1,0
  3942.1    0.05       0  4974.3    0.03       0  4990.3    0.05       0
Bank Sta=4974.3,4990.3
Exp/Cntr=0.3,0.1

Type RM Length L Ch R = 1,17704,373,373,373
BEGIN DESCRIPTION:
Mapping XS 77d96021
END DESCRIPTION:
XS GIS Cut Line= 2
      1644847.07      6863732.18      1644973.64      6864858.70
#Sta/Elev= 30
  4139.1 1864.59  4155.0 1864.15  4162.7 1863.26  4205.3 1862.79  4342.8 1859.60
  4628.0 1854.89  4678.3 1855.52  4703.1 1854.80  4728.6 1854.87  4799.0 1856.18
  4869.5 1855.75  4889.6 1856.32  4899.7 1856.06  4919.8 1853.66  4939.9 1853.91
  4960.0 1852.29  4973.3 1853.11  4990.2 1850.89  4992.3 1850.11  4992.8 1849.61
  5007.8 1849.61  5008.3 1850.11  5010.4 1853.19  5020.4 1856.04  5100.9 1854.58
  5201.6 1856.65  5231.7 1857.91  5243.5 1860.16  5261.9 1867.04  5272.7 1868.10
#Mann=3,-1,0
  4139.1    0.05       0  4992.3    0.03       0  5008.3    0.05       0
Bank Sta=4992.3,5008.3
Exp/Cntr=0.3,0.1

Type RM Length L Ch R = 1,17331,469,469,469
BEGIN DESCRIPTION:
Deadman 64 32.0
END DESCRIPTION:
XS GIS Cut Line= 3
      1644105.01      6863388.03      1644605.00      6864588.00
      1644855.01      6864938.01
#Sta/Elev= 30
  3707.0 1900.30  3891.1 1892.18  4021.1 1882.19  4111.6 1872.42  4212.3 1865.74
  4638.6 1856.32  4684.7 1854.75  4747.0 1850.25  4785.4 1853.26  4867.8 1854.16
  4898.6 1852.25  4952.8 1853.42  4968.5 1852.67  4989.8 1847.78  4990.3 1847.28
  5005.8 1847.78  5010.0 1847.81  5014.3 1850.60  5020.5 1850.01  5029.1 1854.00
  5043.8 1854.48  5079.5 1854.02  5085.6 1855.44  5100.4 1853.82  5142.1 1854.11
  5408.8 1857.54  5415.0 1860.55  5423.6 1861.82  5429.7 1867.65  5437.1 1867.83
#Mann=3,-1,0
  3707.0    0.05       0  4989.8    0.03       0  5005.8    0.05       0
Bank Sta=4989.8,5005.8
Exp/Cntr=0.3,0.1

Type RM Length L Ch R = 1,16862,459,459,459
BEGIN DESCRIPTION:
Deadman 64 31.0
END DESCRIPTION:
XS GIS Cut Line= 3
      1643905.03      6864138.03      1644205.00      6864438.00
      1644905.02      6865638.04
#Sta/Elev= 30
  4576.4 1881.43  4632.9 1875.49  4675.3 1869.24  4682.4 1867.37  4760.2 1858.00
  4929.9 1850.99  4972.3 1851.59  4986.5 1849.60  4989.0 1847.56  4989.5 1847.06
  5005.2 1847.56  5035.8 1849.98  5073.0 1848.59  5094.5 1851.59  5139.5 1852.86
  5255.3 1852.82  5382.2 1850.74  5403.7 1852.15  5446.7 1852.20  5452.5 1852.93
  5475.3 1852.35  5570.0 1854.36  5681.6 1854.30  5753.1 1855.74  5928.0 1862.53
  5996.2 1863.73  6112.0 1867.82  6221.6 1874.92  6286.1 1880.21  6389.9 1885.42
#Mann=3,-1,0
  4576.4    0.05       0  4989.0    0.05       0  5005.2    0.05       0
Bank Sta=4989,5005.2
Exp/Cntr=0.3,0.1

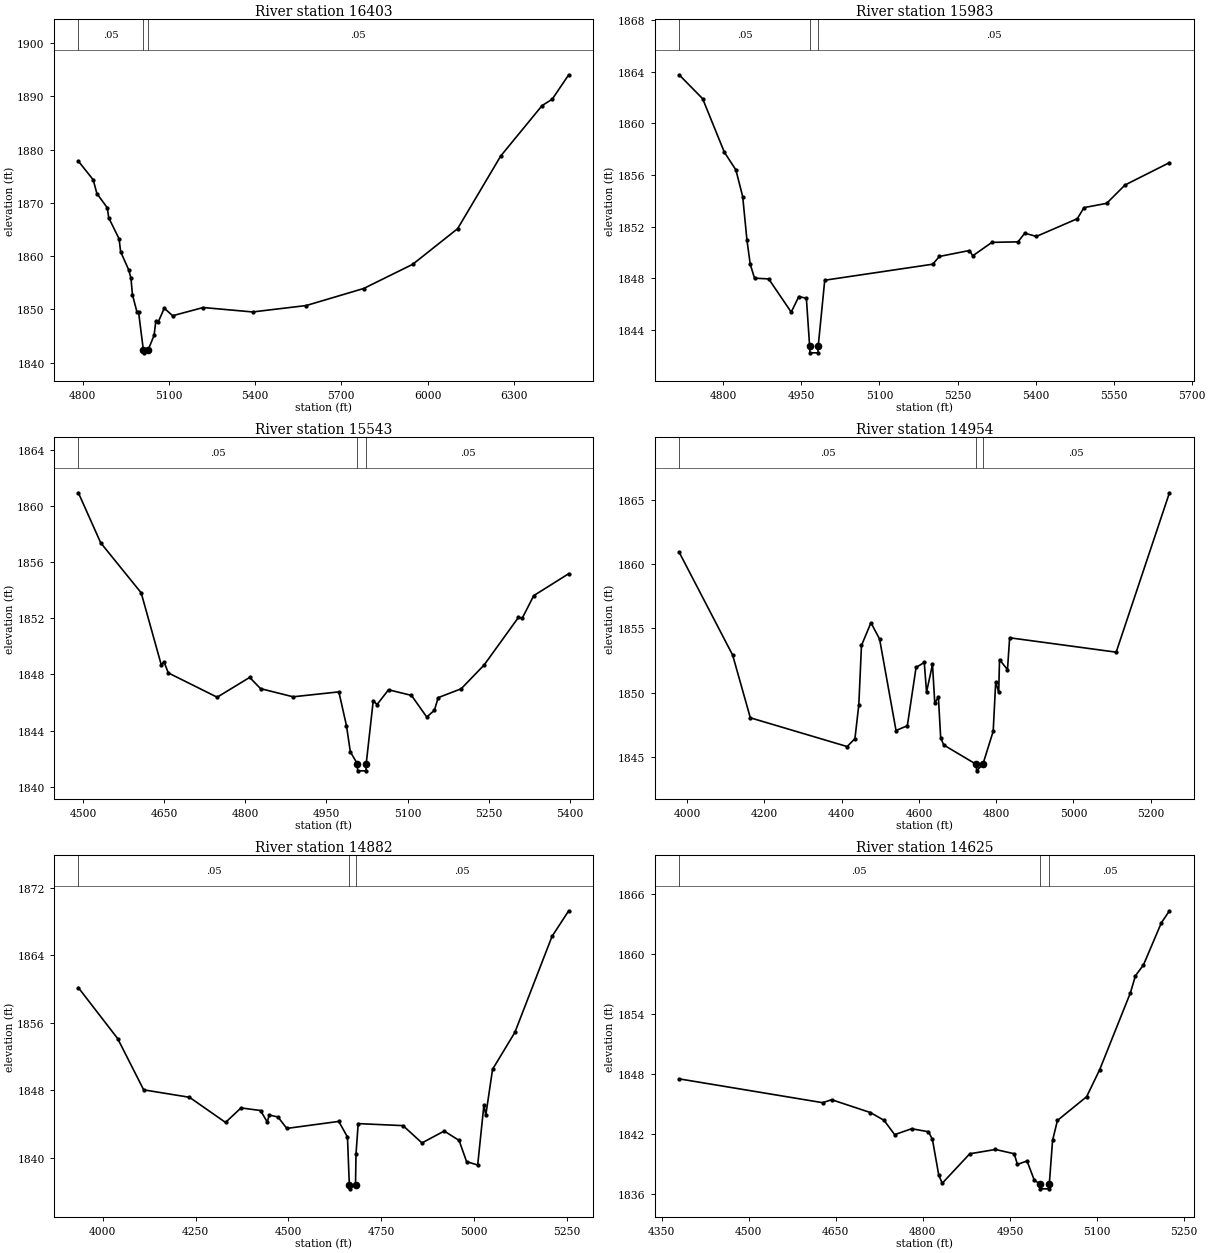
Type RM Length L Ch R = 1,16403,420,420,420
BEGIN DESCRIPTION:
Deadman 64 30.0
END DESCRIPTION:
XS GIS Cut Line= 3
      1643804.99      6864487.98      1643855.00      6864688.00
      1644755.01      6865888.02
#Sta/Elev= 30
  4785.0 1877.84  4836.6 1874.34  4849.4 1871.76  4885.5 1869.09  4890.7 1867.19
  4926.8 1863.24  4931.9 1860.85  4960.3 1857.40  4968.0 1855.85  4973.1 1852.77
  4988.6 1849.57  4994.3 1849.57  5011.2 1842.34  5011.7 1841.84  5027.4 1842.34
  5048.5 1845.13  5054.7 1847.87  5063.1 1847.67  5083.9 1850.22  5113.1 1848.81
  5219.3 1850.35  5391.2 1849.52  5577.6 1850.72  5777.6 1853.92  5948.5 1858.47
  6104.7 1865.16  6254.7 1878.81  6398.5 1888.27  6433.9 1889.48  6491.2 1894.06
#Mann=3,-1,0
  4785.0    0.05       0  5011.2    0.05       0  5027.4    0.05       0
Bank Sta=5011.2,5027.4
Exp/Cntr=0.3,0.1

Type RM Length L Ch R = 1,15983,440,440,440
BEGIN DESCRIPTION:
Mapping XS 24a21763
END DESCRIPTION:
XS GIS Cut Line= 2
      1643568.58      6864922.00      1644315.34      6865496.86
#Sta/Elev= 30
  4714.9 1863.76  4760.1 1861.91  4801.8 1857.77  4824.0 1856.40  4837.1 1854.33
  4845.3 1850.96  4851.6 1849.10  4859.8 1848.02  4887.1 1847.96  4930.4 1845.39
  4945.0 1846.60  4959.5 1846.46  4965.8 1842.74  4966.3 1842.24  4981.7 1842.24
  4982.2 1842.74  4994.8 1847.86  5202.3 1849.10  5215.2 1849.70  5272.9 1850.16
  5279.3 1849.75  5316.1 1850.79  5366.3 1850.83  5379.2 1851.50  5401.6 1851.25
  5480.2 1852.62  5493.1 1853.48  5536.6 1853.81  5571.9 1855.23  5657.3 1856.96
#Mann=3,-1,0
  4714.9    0.05       0  4965.8    0.05       0  4982.2    0.05       0
Bank Sta=4965.8,4982.2
Exp/Cntr=0.3,0.1

Type RM Length L Ch R = 1,15543,589,589,589
BEGIN DESCRIPTION:
Mapping XS a89c133b
END DESCRIPTION:
XS GIS Cut Line= 3
      1643563.66      6864972.23      1643526.39      6865394.58
      1643868.15      6865736.33
#Sta/Elev= 30
  4490.9 1860.92  4532.2 1857.36  4607.1 1853.80  4644.3 1848.67  4649.3 1848.89
  4657.3 1848.10  4747.7 1846.37  4807.9 1847.78  4828.0 1846.98  4888.2 1846.40
  4972.9 1846.75  4987.0 1844.34  4994.1 1842.49  5007.1 1841.63  5007.6 1841.13
  5023.0 1841.13  5023.5 1841.63  5036.5 1846.12  5043.6 1845.85  5064.8 1846.90
  5107.2 1846.50  5135.5 1844.96  5149.7 1845.44  5156.7 1846.34  5199.2 1846.97
  5241.6 1848.66  5305.2 1852.05  5312.3 1852.00  5333.5 1853.60  5398.2 1855.16
#Mann=3,-1,0
  4490.9    0.05       0  5007.1    0.03       0  5023.5    0.05       0
Bank Sta=5007.1,5023.5
Exp/Cntr=0.3,0.1

Type RM Length L Ch R = 1,14954,72,72,72
BEGIN DESCRIPTION:
Mapping XS a37ca4db
END DESCRIPTION:
XS GIS Cut Line= 6
      1643520.60      6864964.27      1643484.20      6865436.77
      1643294.33      6865554.91      1643209.94      6865656.18
      1643171.97      6865732.13      1643205.50      6866084.81
#Sta/Elev= 30
  3979.3 1860.94  4117.9 1852.92  4163.6 1848.04  4414.3 1845.80  4434.4 1846.42
  4444.4 1849.05  4451.3 1853.67  4475.8 1855.44  4498.2 1854.17  4540.7 1847.05
  4570.0 1847.42  4592.6 1851.96  4613.8 1852.35  4619.7 1850.04  4635.1 1852.19
  4641.0 1849.19  4650.4 1849.65  4656.3 1846.48  4664.3 1845.92  4748.7 1844.41
  4749.2 1843.91  4765.4 1844.41  4792.2 1846.99  4798.7 1850.84  4806.5 1850.02
  4808.6 1852.57  4829.2 1851.79  4834.8 1854.27  5110.5 1853.15  5248.4 1865.56
#Mann=3,-1,0
  3979.3    0.05       0  4748.7    0.03       0  4765.4    0.05       0
Bank Sta=4748.7,4765.4
Exp/Cntr=0.3,0.1

Type RM Length L Ch R = 1,14882,257,257,257
BEGIN DESCRIPTION:
Mapping XS ada1adcb
END DESCRIPTION:
XS GIS Cut Line= 6
      1643489.87      6864972.47      1643461.19      6865400.62
      1643270.69      6865482.55      1643162.12      6865548.10
      1643108.86      6865656.67      1643090.43      6866092.95
#Sta/Elev= 30
  3934.4 1860.16  4040.2 1854.13  4110.3 1848.05  4233.7 1847.17  4330.8 1844.19
  4372.6 1845.91  4425.1 1845.60  4443.2 1844.24  4448.7 1845.07  4472.2 1844.83
  4495.8 1843.48  4635.9 1844.31  4659.3 1842.46  4664.3 1836.82  4664.8 1836.32
  4681.0 1836.82  4682.3 1840.44  4688.2 1844.05  4809.0 1843.81  4860.0 1841.76
  4920.0 1843.17  4960.1 1842.05  4980.1 1839.55  5010.1 1839.14  5026.9 1846.27
  5031.9 1845.04  5050.2 1850.49  5110.2 1854.85  5210.3 1866.23  5255.3 1869.27
#Mann=3,-1,0
  3934.4    0.05       0  4664.3    0.05       0  4681.0    0.05       0
Bank Sta=4664.3,4681
Exp/Cntr=0.3,0.1

Type RM Length L Ch R = 1,14625,419,419,419
BEGIN DESCRIPTION:
Deadman 64 29.0
END DESCRIPTION:
XS GIS Cut Line= 3
      1643146.66      6865116.08      1642905.00      6865688.00
      1642804.99      6865888.01
#Sta/Elev= 30
  4380.2 1847.52  4627.5 1845.14  4642.8 1845.44  4709.5 1844.16  4733.2 1843.38
  4751.4 1841.95  4780.6 1842.54  4809.7 1842.24  4816.5 1841.47  4827.4 1837.90
  4833.4 1837.10  4880.8 1840.04  4925.1 1840.47  4957.4 1840.04  4962.8 1838.98
  4979.4 1839.32  4991.9 1837.41  5001.1 1837.04  5001.6 1836.54  5017.3 1836.54
  5017.8 1837.04  5023.4 1841.37  5031.8 1843.37  5082.1 1845.74  5104.5 1848.43
  5157.6 1856.13  5166.0 1857.80  5180.0 1858.90  5210.7 1863.09  5224.7 1864.30
#Mann=3,-1,0
  4380.2    0.05       0  5001.1    0.05       0  5017.8    0.05       0
Bank Sta=5001.1,5017.8
Exp/Cntr=0.3,0.1

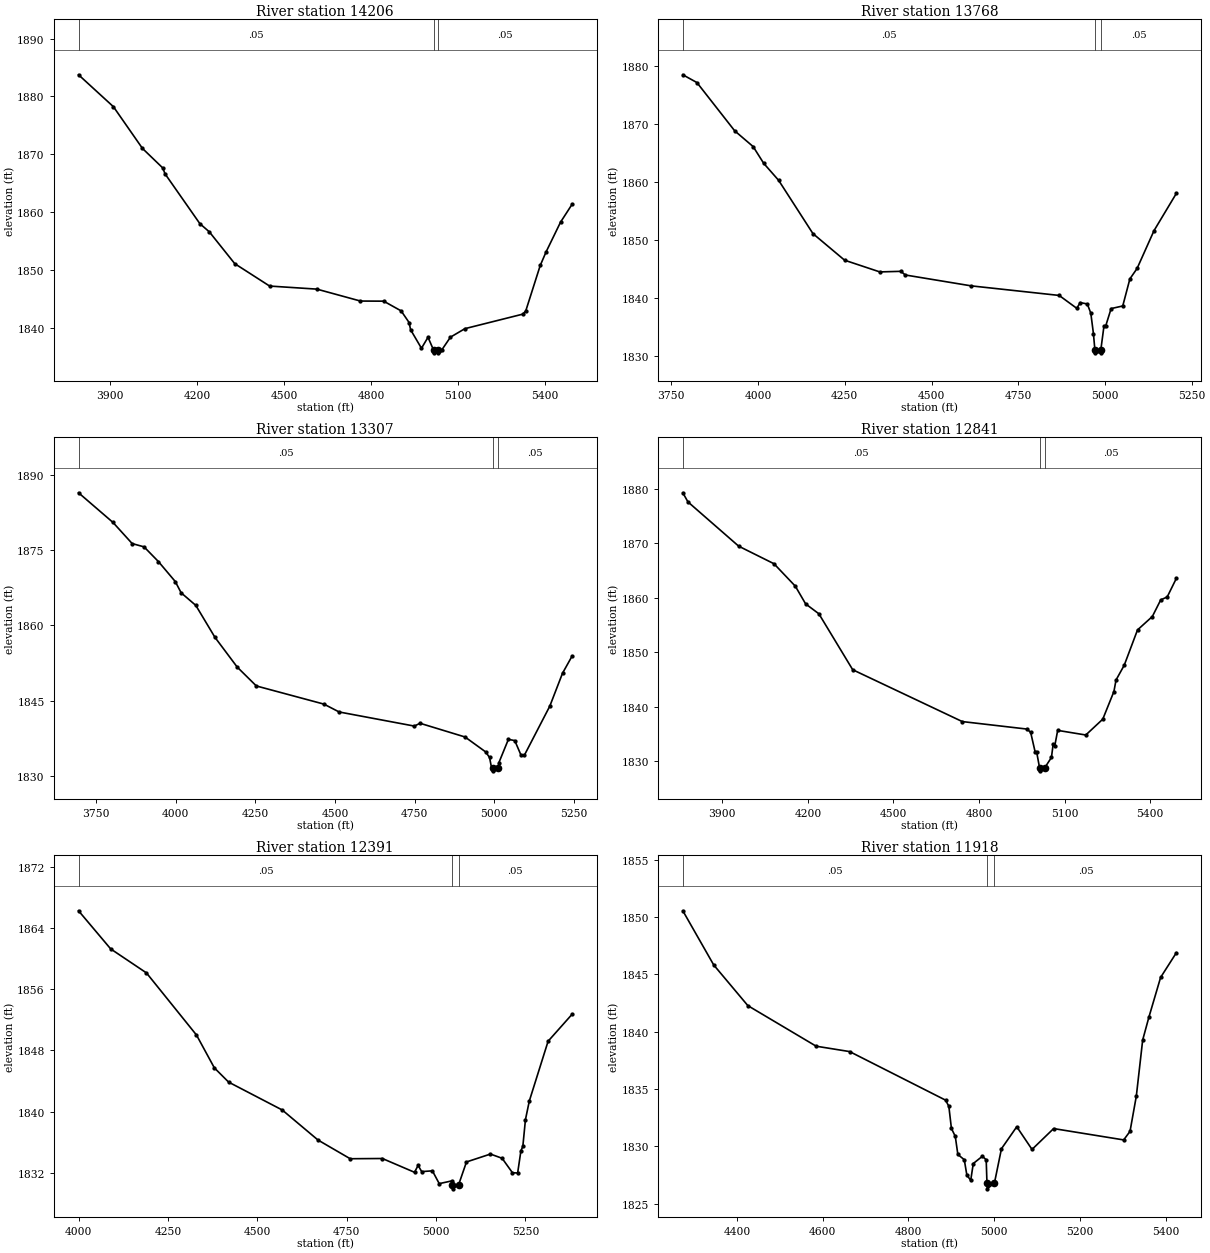
Type RM Length L Ch R = 1,14206,438,438,438
BEGIN DESCRIPTION:
Deadman 64 28.0
END DESCRIPTION:
XS GIS Cut Line= 3
      1642605.00      6864137.96      1642705.00      6865338.00
      1642705.00      6865838.00
#Sta/Elev= 30
  3790.3 1883.74  3910.8 1878.22  4011.1 1871.01  4081.3 1867.63  4088.9 1866.63
  4209.3 1858.01  4241.9 1856.60  4329.7 1851.10  4450.1 1847.23  4613.2 1846.70
  4763.7 1844.64  4844.0 1844.62  4904.2 1842.94  4931.8 1840.92  4936.8 1839.69
  4974.4 1836.48  4997.0 1838.38  5016.0 1836.19  5016.5 1835.69  5032.5 1835.69
  5033.0 1836.19  5044.5 1836.19  5074.5 1838.40  5124.5 1839.87  5324.5 1842.38
  5334.5 1842.93  5384.5 1850.79  5404.5 1853.11  5454.5 1858.26  5494.5 1861.36
#Mann=3,-1,0
  3790.3    0.05       0  5016.0    0.03       0  5033.0    0.05       0
Bank Sta=5016,5033
Exp/Cntr=0.3,0.1

Type RM Length L Ch R = 1,13768,461,461,461
BEGIN DESCRIPTION:
Deadman 64 27.0
END DESCRIPTION:
XS GIS Cut Line= 3
      1642505.01      6864237.96      1642305.00      6865438.00
      1642255.01      6865637.95
#Sta/Elev= 30
  3783.1 1878.50  3823.7 1877.16  3932.7 1868.82  3985.9 1866.10  4016.3 1863.21
  4059.4 1860.27  4158.2 1851.08  4249.5 1846.49  4350.9 1844.47  4411.7 1844.57
  4424.4 1843.94  4614.5 1842.06  4867.9 1840.41  4918.6 1838.19  4928.7 1839.17
  4949.0 1838.94  4959.1 1837.36  4966.7 1833.83  4970.9 1831.00  4971.4 1830.50
  4987.5 1830.50  4988.0 1831.00  4997.2 1835.18  5002.3 1835.18  5017.7 1838.14
  5051.2 1838.59  5071.8 1843.27  5092.5 1845.06  5141.4 1851.60  5205.8 1858.03
#Mann=3,-1,0
  3783.1    0.05       0  4970.9    0.03       0  4988.0    0.05       0
Bank Sta=4970.9,4988
Exp/Cntr=0.3,0.1

Type RM Length L Ch R = 1,13307,466,466,466
BEGIN DESCRIPTION:
Deadman 64 26.0
END DESCRIPTION:
XS GIS Cut Line= 3
      1642404.99      6864088.03      1641905.00      6865288.00
      1641905.00      6865538.03
#Sta/Elev= 30
  3694.5 1886.42  3802.8 1880.51  3862.9 1876.31  3900.3 1875.65  3945.3 1872.73
  3998.3 1868.75  4016.8 1866.50  4062.8 1864.00  4122.9 1857.64  4192.8 1851.72
  4252.9 1847.96  4465.3 1844.34  4512.9 1842.78  4749.1 1839.97  4767.0 1840.53
  4908.3 1837.80  4972.8 1834.84  4985.3 1833.72  4991.8 1831.59  4995.9 1831.56
  4996.4 1831.06  5013.1 1831.56  5014.5 1832.67  5044.5 1837.33  5064.5 1837.08
  5084.5 1834.12  5094.5 1834.15  5174.5 1843.94  5214.5 1850.50  5244.5 1853.91
#Mann=3,-1,0
  3694.5    0.05       0  4995.9    0.03       0  5013.1    0.05       0
Bank Sta=4995.9,5013.1
Exp/Cntr=0.3,0.1

Type RM Length L Ch R = 1,12841,450,450,450
BEGIN DESCRIPTION:
Deadman 64 25.0
END DESCRIPTION:
XS GIS Cut Line= 3
      1641755.00      6864038.02      1641455.00      6865238.00
      1641655.02      6865688.04
#Sta/Elev= 30
  3762.0 1879.32  3780.0 1877.64  3957.8 1869.50  4081.5 1866.27  4156.3 1862.14
  4192.3 1858.89  4238.7 1857.07  4357.3 1846.78  4741.2 1837.25  4968.0 1835.87
  4980.9 1835.25  4996.3 1831.71  5001.6 1831.71  5012.2 1828.69  5012.7 1828.19
  5029.4 1828.69  5053.6 1830.65  5059.8 1833.13  5065.3 1832.79  5075.5 1835.63
  5174.0 1834.78  5233.5 1837.69  5272.5 1842.77  5280.0 1844.90  5308.7 1847.61
  5355.2 1854.10  5407.2 1856.57  5436.6 1859.63  5459.2 1860.16  5491.4 1863.59
#Mann=3,-1,0
  3762.0    0.05       0  5012.2    0.05       0  5029.4    0.05       0
Bank Sta=5012.2,5029.4
Exp/Cntr=0.3,0.1

Type RM Length L Ch R = 1,12391,473,473,473
BEGIN DESCRIPTION:
Deadman 64 24.0
END DESCRIPTION:
XS GIS Cut Line= 3
      1641055.00      6864287.96      1641055.00      6865288.00
      1641204.99      6865637.97
#Sta/Elev= 30
  3999.9 1866.22  4089.9 1861.24  4189.9 1858.11  4329.9 1850.00  4379.9 1845.71
  4419.9 1843.85  4569.9 1840.21  4669.9 1836.29  4759.9 1833.85  4849.9 1833.88
  4939.9 1832.08  4949.9 1832.98  4959.9 1832.17  4989.9 1832.27  5009.0 1830.60
  5043.5 1830.95  5045.7 1830.42  5046.2 1829.92  5063.0 1830.42  5085.2 1833.43
  5152.3 1834.46  5184.9 1833.91  5213.9 1832.02  5228.4 1831.99  5237.5 1834.88
  5242.9 1835.46  5250.2 1838.95  5261.1 1841.40  5313.6 1849.19  5380.7 1852.71
#Mann=3,-1,0
  3999.9    0.05       0  5045.7    0.03       0  5063.0    0.05       0
Bank Sta=5045.7,5063
Exp/Cntr=0.3,0.1

Type RM Length L Ch R = 1,11918,485,485,485
BEGIN DESCRIPTION:
Deadman 64 23.0
END DESCRIPTION:
XS GIS Cut Line= 3
      1640255.00      6864688.00      1640655.00      6865288.00
      1640904.99      6865637.98
#Sta/Elev= 30
  4273.8 1850.56  4345.9 1845.83  4425.5 1842.28  4584.8 1838.74  4662.9 1838.27
  4886.7 1834.03  4894.3 1833.49  4900.3 1831.56  4909.3 1830.87  4915.3 1829.29
  4930.3 1828.83  4936.3 1827.49  4945.3 1827.03  4951.3 1828.50  4972.4 1829.13
  4981.4 1828.83  4983.2 1826.79  4983.7 1826.29  5000.6 1826.79  5017.0 1829.79
  5052.7 1831.71  5088.3 1829.73  5138.7 1831.55  5302.1 1830.56  5316.9 1831.31
  5331.6 1834.39  5346.4 1839.28  5361.1 1841.30  5388.2 1844.74  5425.0 1846.90
#Mann=3,-1,0
  4273.8    0.05       0  4983.2    0.03       0  5000.6    0.05       0
Bank Sta=4983.2,5000.6
Exp/Cntr=0.3,0.1

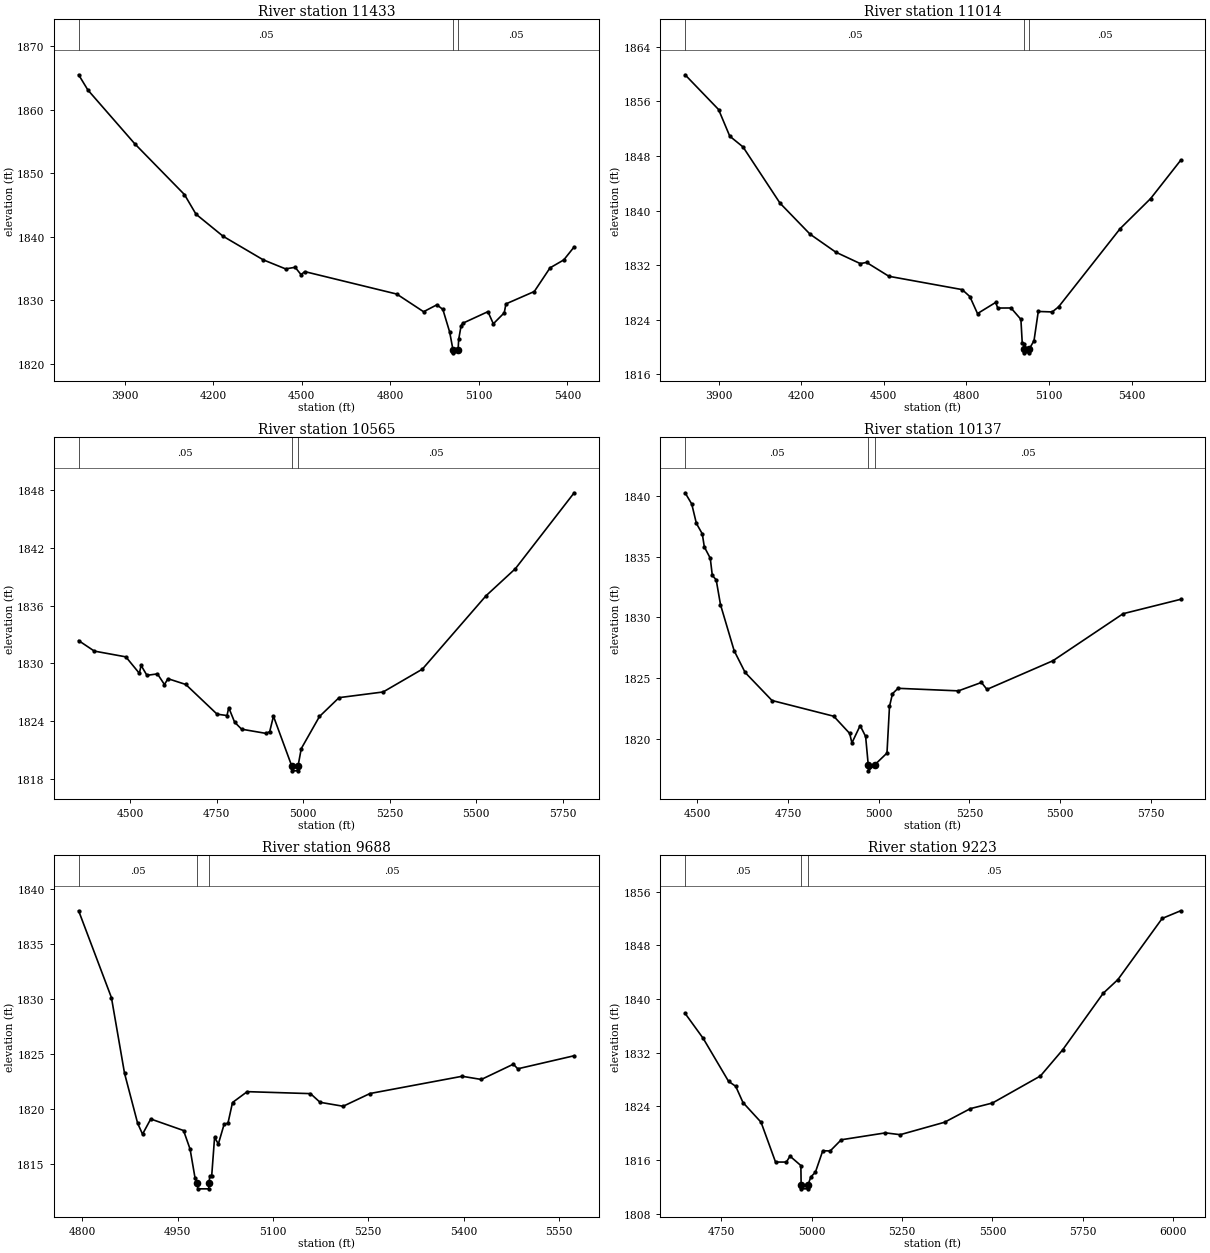
Type RM Length L Ch R = 1,11433,419,419,419
BEGIN DESCRIPTION:
Deadman 64 22.0
END DESCRIPTION:
XS GIS Cut Line= 3
      1640055.01      6864438.04      1640425.42      6865639.29
      1640572.92      6866034.60
#Sta/Elev= 30
  3743.7 1865.48  3775.1 1863.08  3933.8 1854.63  4102.3 1846.63  4141.3 1843.55
  4233.0 1840.08  4368.9 1836.37  4444.8 1834.94  4477.4 1835.19  4497.1 1834.04
  4510.0 1834.51  4821.5 1830.98  4912.5 1828.20  4957.6 1829.29  4977.8 1828.56
  5000.8 1825.01  5012.0 1822.23  5012.5 1821.73  5029.4 1822.23  5031.4 1823.84
  5039.6 1825.99  5044.9 1826.38  5130.5 1828.21  5148.8 1826.30  5185.8 1828.03
  5191.5 1829.43  5287.6 1831.38  5340.9 1835.10  5387.4 1836.35  5422.7 1838.40
#Mann=3,-1,0
  3743.7    0.05       0  5012.0    0.05       0  5029.4    0.05       0
Bank Sta=5012,5029.4
Exp/Cntr=0.3,0.1

Type RM Length L Ch R = 1,11014,449,449,449
BEGIN DESCRIPTION:
Deadman 64 21.0
END DESCRIPTION:
XS GIS Cut Line= 3
      1639855.00      6864588.01      1640055.00      6865788.00
      1640354.98      6866287.97
#Sta/Elev= 30
  3778.6 1859.88  3900.2 1854.79  3940.8 1850.89  3989.0 1849.31  4123.3 1841.08
  4232.3 1836.54  4326.0 1833.90  4414.7 1832.23  4437.6 1832.40  4518.7 1830.37
  4784.8 1828.42  4812.7 1827.40  4840.5 1824.91  4906.4 1826.54  4914.0 1825.72
  4962.2 1825.73  4998.1 1824.06  5002.9 1820.64  5008.7 1820.39  5009.4 1819.66
  5009.9 1819.16  5027.0 1819.16  5027.5 1819.66  5045.7 1820.94  5061.2 1825.22
  5111.8 1825.15  5135.1 1825.90  5358.6 1837.35  5469.4 1841.76  5578.2 1847.35
#Mann=3,-1,0
  3778.6    0.05       0  5009.4    0.03       0  5027.5    0.05       0
Bank Sta=5009.4,5027.5
Exp/Cntr=0.3,0.1

Type RM Length L Ch R = 1,10565,428,428,428
BEGIN DESCRIPTION:
Deadman 64 20.0
END DESCRIPTION:
XS GIS Cut Line= 3
      1639551.73      6865293.28      1639655.00      6865938.00
      1640205.03      6866488.03
#Sta/Elev= 30
  4351.7 1832.37  4397.0 1831.28  4488.1 1830.68  4527.0 1828.97  4532.1 1829.79
  4548.9 1828.76  4579.3 1828.91  4599.5 1827.80  4609.7 1828.41  4661.1 1827.81
  4751.5 1824.72  4780.1 1824.58  4785.1 1825.40  4802.1 1823.89  4822.3 1823.16
  4893.2 1822.72  4903.4 1822.91  4914.2 1824.51  4967.1 1819.33  4967.6 1818.83
  4984.7 1818.83  4985.2 1819.33  4994.5 1821.14  5047.1 1824.48  5103.6 1826.44
  5230.9 1827.03  5344.1 1829.40  5527.9 1837.03  5612.8 1839.85  5782.5 1847.74
#Mann=3,-1,0
  4351.7    0.05       0  4967.1    0.03       0  4985.2    0.05       0
Bank Sta=4967.1,4985.2
Exp/Cntr=0.3,0.1

Type RM Length L Ch R = 1,10137,449,449,449
BEGIN DESCRIPTION:
Deadman 64 19.0
END DESCRIPTION:
XS GIS Cut Line= 3
      1639007.43      6865571.79      1639255.00      6866038.00
      1639707.27      6866743.88
#Sta/Elev= 30
  4466.3 1840.23  4484.6 1839.31  4497.4 1837.72  4513.7 1836.86  4519.3 1835.79
  4535.7 1834.86  4541.3 1833.45  4552.0 1833.09  4563.9 1831.05  4601.6 1827.27
  4631.8 1825.49  4705.9 1823.19  4876.1 1821.90  4920.0 1820.49  4926.2 1819.71
  4948.9 1821.13  4964.0 1820.24  4971.2 1817.92  4971.7 1817.42  4989.4 1817.92
  5022.9 1818.88  5029.8 1822.70  5038.1 1823.75  5053.3 1824.19  5219.8 1823.98
  5283.3 1824.67  5298.5 1824.10  5480.3 1826.45  5673.9 1830.31  5832.5 1831.49
#Mann=3,-1,0
  4466.3    0.05       0  4971.2    0.05       0  4989.4    0.05       0
Bank Sta=4971.2,4989.4
Exp/Cntr=0.3,0.1

Type RM Length L Ch R = 1,9688,465,465,465
BEGIN DESCRIPTION:
Deadman 64 18.0
END DESCRIPTION:
XS GIS Cut Line= 3
      1638804.99      6865937.97      1638855.00      6866138.00
      1639167.79      6866618.23
#Sta/Elev= 30
  4794.5 1838.02  4846.1 1830.11  4866.7 1823.22  4887.3 1818.67  4895.0 1817.68
  4907.9 1819.06  4959.5 1818.01  4969.8 1816.31  4977.5 1813.71  4981.3 1813.20
  4981.8 1812.70  4999.0 1812.70  4999.5 1813.20  5000.7 1813.83  5003.7 1813.83
  5008.3 1817.39  5014.2 1816.78  5023.4 1818.60  5029.3 1818.67  5036.5 1820.56
  5059.6 1821.55  5159.1 1821.37  5174.2 1820.58  5210.5 1820.22  5252.7 1821.38
  5397.6 1822.95  5427.8 1822.66  5478.1 1824.05  5485.1 1823.63  5573.8 1824.82
#Mann=3,-1,0
  4794.5    0.05       0  4981.3    0.05       0  4999.5    0.05       0
Bank Sta=4981.3,4999.5
Exp/Cntr=0.3,0.1

Type RM Length L Ch R = 1,9223,488,488,488
BEGIN DESCRIPTION:
Deadman 64 17.0
END DESCRIPTION:
XS GIS Cut Line= 3
      1638505.00      6866038.03      1638505.00      6866388.00
      1638705.00      6867388.02
#Sta/Elev= 30
  4650.3 1837.87  4700.3 1834.15  4770.3 1827.76  4790.3 1827.00  4810.3 1824.59
  4860.3 1821.65  4900.3 1815.72  4930.3 1815.72  4940.3 1816.60  4970.3 1815.20
  4971.1 1812.23  4971.6 1811.73  4989.0 1811.73  4989.5 1812.23  4997.8 1813.50
  5010.5 1814.21  5030.9 1817.41  5051.3 1817.37  5081.9 1819.04  5204.2 1820.07
  5245.0 1819.80  5367.4 1821.65  5438.8 1823.68  5500.0 1824.52  5632.6 1828.55
  5693.7 1832.42  5805.9 1840.86  5846.7 1842.91  5969.1 1852.02  6020.1 1853.16
#Mann=3,-1,0
  4650.3    0.05       0  4971.1    0.05       0  4989.5    0.05       0
Bank Sta=4971.1,4989.5
Exp/Cntr=0.3,0.1