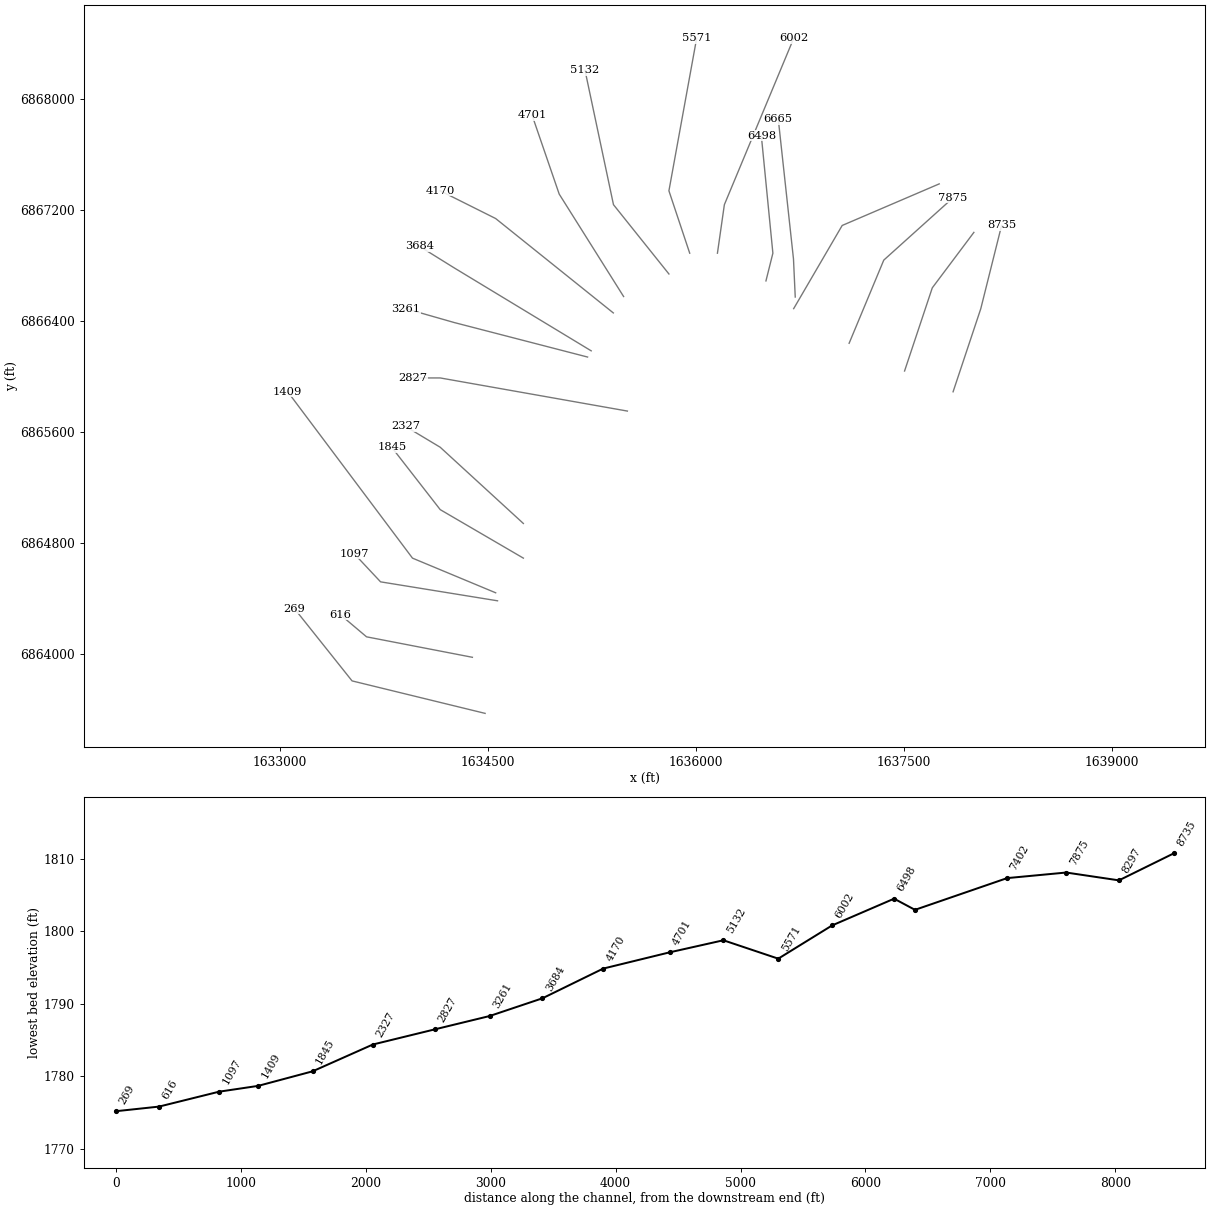
HEC-RAS study Deadman 64.prj: Deadman 64 Base Level Engineering

--- Deadman 64.g01 (geometry) --- (continued)

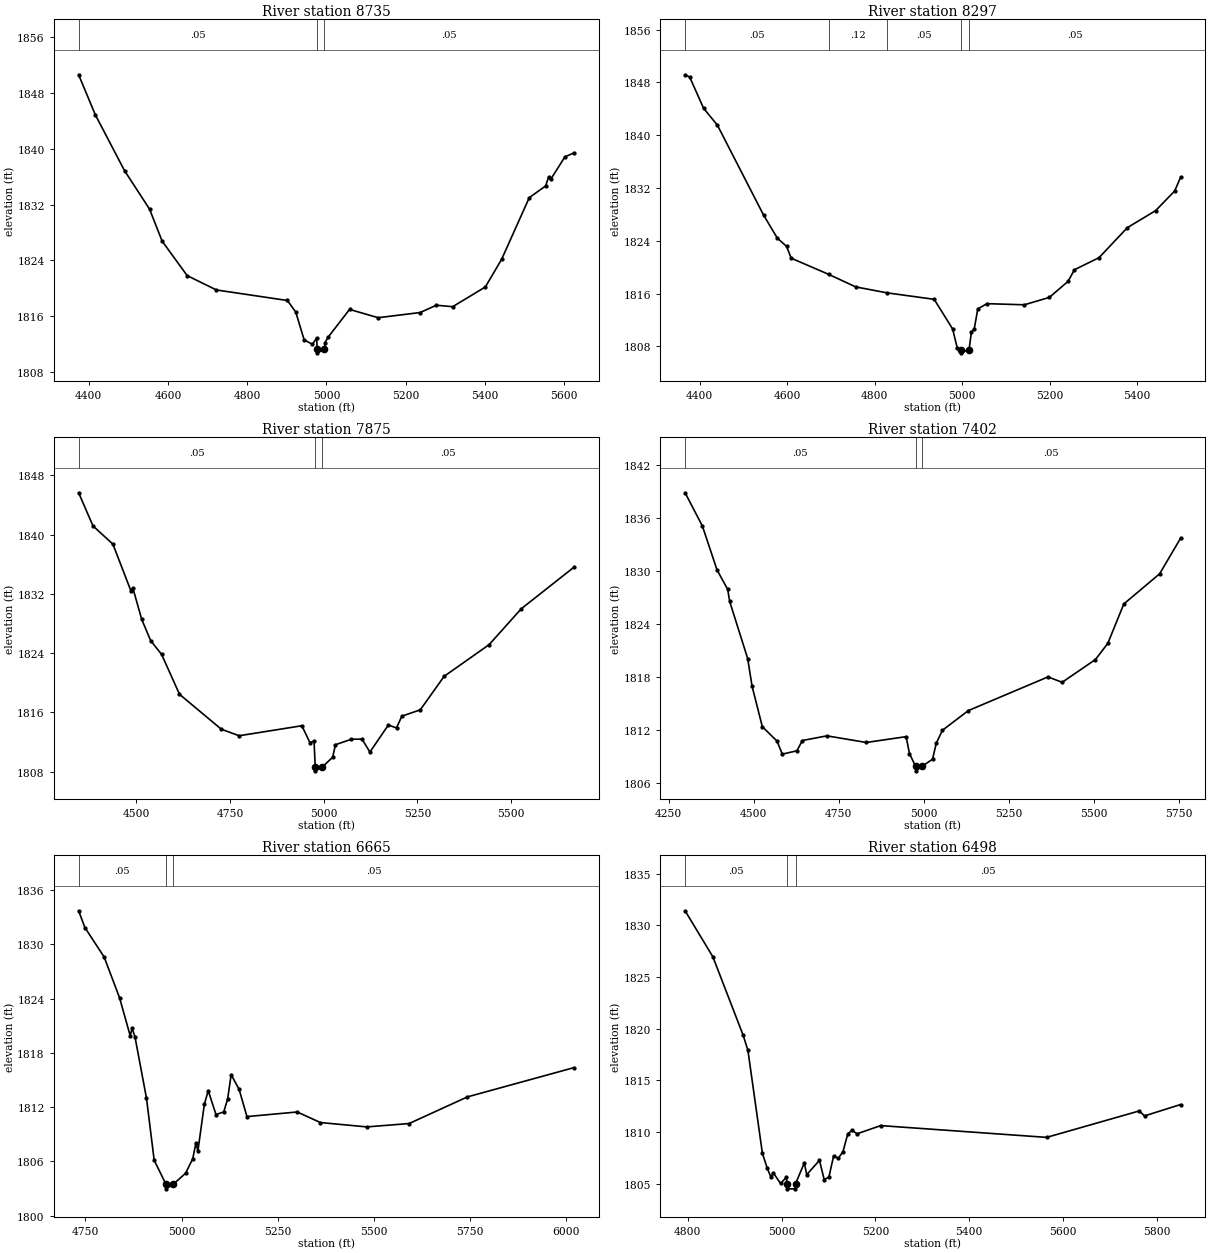
Type RM Length L Ch R = 1,8735,438,438,438
BEGIN DESCRIPTION:
Deadman 64 16.0
END DESCRIPTION:
XS GIS Cut Line= 3
      1637855.02      6865888.05      1638055.00      6866488.00
      1638205.01      6867088.03
#Sta/Elev= 30
  4374.5 1850.64  4416.6 1844.90  4490.4 1836.88  4553.6 1831.36  4585.3 1826.77
  4648.5 1821.83  4722.3 1819.77  4901.5 1818.26  4922.6 1816.60  4943.7 1812.62
  4964.7 1811.97  4975.3 1812.88  4976.6 1811.25  4977.1 1810.75  4995.1 1811.25
  4996.4 1812.22  5004.3 1813.00  5058.4 1816.98  5130.6 1815.79  5236.3 1816.53
  5277.5 1817.58  5318.7 1817.37  5401.2 1820.20  5442.4 1824.18  5512.0 1833.01
  5553.2 1834.69  5560.9 1835.97  5566.1 1835.64  5602.2 1838.88  5625.4 1839.44
#Mann=3,-1,0
  4374.5    0.05       0  4976.6    0.03       0  4995.1    0.05       0
Bank Sta=4976.6,4995.1
Exp/Cntr=0.3,0.1

Type RM Length L Ch R = 1,8297,422,422,422
BEGIN DESCRIPTION:
Deadman 64 15.0
END DESCRIPTION:
XS GIS Cut Line= 3
      1637505.00      6866037.99      1637705.00      6866638.00
      1638005.02      6867038.03
#Sta/Elev= 30
  4367.0 1849.16  4377.5 1848.81  4409.2 1844.09  4440.8 1841.53  4546.2 1827.92
  4577.8 1824.41  4598.9 1823.16  4609.5 1821.37  4694.8 1818.93  4757.0 1817.02
  4828.4 1816.12  4936.2 1815.14  4978.4 1810.65  4988.9 1807.78  4997.5 1807.53
  4998.0 1807.03  5016.0 1807.53  5021.3 1810.17  5027.6 1810.58  5035.9 1813.68
  5056.8 1814.48  5142.2 1814.31  5199.5 1815.43  5242.2 1817.86  5256.8 1819.62
  5313.0 1821.45  5377.6 1825.99  5442.2 1828.57  5485.9 1831.55  5499.5 1833.65
#Mann=5,-1,0
  4367.0    0.05       0  4694.8    0.12       0  4828.4    0.05       0
  4997.5    0.05       0  5016.0    0.05       0
Bank Sta=4997.5,5016
Exp/Cntr=0.3,0.1

Type RM Length L Ch R = 1,7875,473,473,473
BEGIN DESCRIPTION:
Deadman 64 14.0
END DESCRIPTION:
XS GIS Cut Line= 3
      1637105.01      6866238.03      1637355.00      6866838.00
      1637854.96      6867287.97
#Sta/Elev= 30
  4345.6 1845.66  4384.0 1841.18  4437.1 1838.72  4484.8 1832.46  4490.2 1832.82
  4514.0 1828.56  4537.9 1825.69  4567.1 1823.83  4614.8 1818.45  4726.4 1813.73
  4774.0 1812.85  4941.4 1814.20  4963.1 1811.90  4973.9 1812.15  4977.1 1808.61
  4977.6 1808.11  4995.6 1808.61  5023.6 1809.95  5031.1 1811.64  5073.7 1812.38
  5102.1 1812.39  5123.0 1810.64  5172.3 1814.30  5194.0 1813.90  5208.2 1815.49
  5257.5 1816.35  5321.1 1820.87  5441.4 1825.16  5526.6 1829.98  5668.2 1835.63
#Mann=3,-1,0
  4345.6    0.05       0  4977.1    0.03       0  4995.6    0.05       0
Bank Sta=4977.1,4995.6
Exp/Cntr=0.3,0.1

Type RM Length L Ch R = 1,7402,737,737,737
BEGIN DESCRIPTION:
Deadman 64 13.0
END DESCRIPTION:
XS GIS Cut Line= 3
      1636705.02      6866488.04      1637055.00      6867088.00
      1637755.04      6867388.02
#Sta/Elev= 30
  4298.2 1838.81  4349.0 1835.05  4392.0 1830.08  4423.4 1827.87  4429.2 1826.51
  4482.1 1820.05  4495.0 1816.92  4525.1 1812.34  4568.2 1810.71  4583.9 1809.23
  4626.9 1809.61  4642.6 1810.77  4714.9 1811.30  4830.7 1810.55  4947.7 1811.21
  4957.6 1809.29  4975.7 1807.84  4976.2 1807.34  4994.2 1807.84  5025.4 1808.66
  5036.3 1810.47  5054.4 1811.93  5130.6 1814.16  5364.5 1817.97  5406.2 1817.36
  5504.1 1819.94  5540.4 1821.77  5587.5 1826.23  5692.7 1829.64  5754.4 1833.68
#Mann=3,-1,0
  4298.2    0.05       0  4975.7    0.03       0  4994.2    0.05       0
Bank Sta=4975.7,4994.2
Exp/Cntr=0.3,0.1

Type RM Length L Ch R = 1,6665,167,167,167
BEGIN DESCRIPTION:
Mapping XS 92db5489
END DESCRIPTION:
XS GIS Cut Line= 3
      1636716.31      6866571.80      1636703.65      6866846.05
      1636594.02      6867853.76
#Sta/Elev= 30
  4732.5 1833.71  4748.7 1831.86  4798.8 1828.60  4838.8 1824.10  4866.5 1819.90
  4871.6 1820.71  4878.9 1819.78  4908.9 1812.98  4928.9 1806.12  4959.6 1803.46
  4960.1 1802.96  4978.3 1803.46  5010.5 1804.68  5029.1 1806.28  5037.5 1808.05
  5042.5 1807.13  5059.3 1812.31  5069.4 1813.82  5089.5 1811.18  5109.6 1811.46
  5119.7 1812.86  5129.0 1815.59  5149.8 1813.95  5170.0 1810.95  5300.7 1811.46
  5361.1 1810.29  5481.8 1809.81  5591.5 1810.18  5743.3 1813.13  6020.7 1816.37
#Mann=3,-1,0
  4732.5    0.05       0  4959.6    0.03       0  4978.3    0.05       0
Bank Sta=4959.6,4978.3
Exp/Cntr=0.3,0.1

Type RM Length L Ch R = 1,6498,496,496,496
BEGIN DESCRIPTION:
Deadman 64 12.0
END DESCRIPTION:
XS GIS Cut Line= 3
      1636504.99      6866687.98      1636555.00      6866888.00
      1636471.75      6867734.64
#Sta/Elev= 30
  4794.3 1831.41  4853.6 1826.95  4918.0 1819.38  4928.3 1817.90  4959.2 1807.93
  4969.6 1806.49  4977.3 1805.64  4982.4 1806.05  4997.9 1805.02  5010.5 1805.63
  5011.2 1805.00  5011.7 1804.50  5029.4 1804.50  5029.9 1805.00  5048.6 1807.01
  5053.7 1805.87  5080.9 1807.26  5090.9 1805.40  5101.0 1805.63  5111.0 1807.68
  5121.1 1807.46  5131.1 1808.11  5141.2 1809.81  5150.0 1810.16  5161.3 1809.83
  5211.5 1810.62  5565.4 1809.48  5763.0 1812.04  5774.2 1811.56  5851.2 1812.66
#Mann=3,-1,0
  4794.3    0.05       0  5011.2    0.03       0  5029.9    0.05       0
Bank Sta=5011.2,5029.9
Exp/Cntr=0.3,0.1

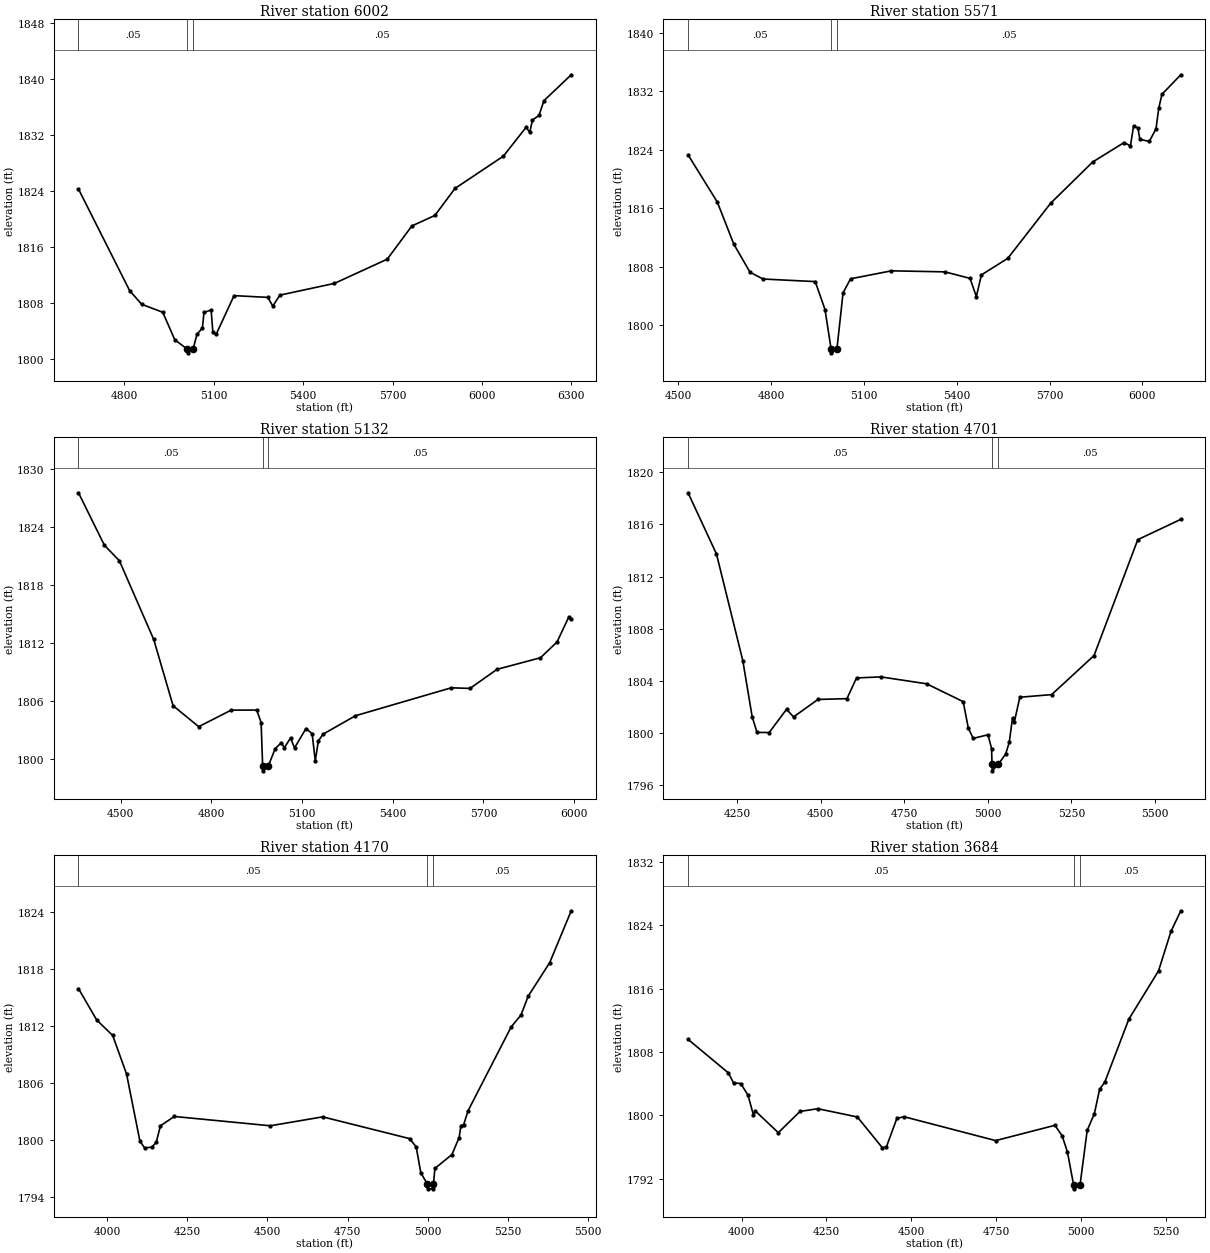
Type RM Length L Ch R = 1,6002,431,431,431
BEGIN DESCRIPTION:
Deadman 64 11.0
END DESCRIPTION:
XS GIS Cut Line= 3
      1636155.00      6866888.03      1636205.00      6867238.00
      1636704.99      6868437.98
#Sta/Elev= 30
  4646.0 1824.23  4817.7 1809.70  4858.1 1807.75  4928.8 1806.61  4969.2 1802.68
  5011.8 1801.31  5012.3 1800.81  5030.5 1801.31  5043.4 1803.45  5061.8 1804.35
  5067.2 1806.59  5091.1 1806.94  5097.0 1803.72  5107.9 1803.45  5168.0 1808.99
  5281.2 1808.74  5298.0 1807.50  5321.8 1809.06  5504.9 1810.74  5682.0 1814.20
  5764.9 1818.96  5841.8 1820.45  5909.5 1824.32  6072.0 1828.94  6147.9 1833.06
  6160.3 1832.34  6169.5 1834.11  6191.2 1834.75  6208.0 1836.87  6299.5 1840.57
#Mann=3,-1,0
  4646.0    0.05       0  5011.8    0.03       0  5030.5    0.05       0
Bank Sta=5011.8,5030.5
Exp/Cntr=0.3,0.1

Type RM Length L Ch R = 1,5571,439,439,439
BEGIN DESCRIPTION:
Deadman 64 10.0
END DESCRIPTION:
XS GIS Cut Line= 3
      1635955.00      6866888.01      1635805.00      6867338.00
      1636005.01      6868438.03
#Sta/Elev= 30
  4531.6 1823.29  4626.5 1816.81  4679.2 1811.10  4731.9 1807.24  4774.0 1806.31
  4942.7 1805.96  4974.3 1802.13  4994.0 1796.72  4994.5 1796.22  5012.7 1796.72
  5032.6 1804.42  5056.8 1806.34  5188.9 1807.43  5361.7 1807.29  5443.0 1806.40
  5463.3 1803.91  5479.8 1806.88  5565.0 1809.14  5703.4 1816.67  5839.4 1822.31
  5941.0 1824.97  5961.3 1824.51  5971.5 1827.23  5985.5 1826.96  5991.8 1825.40
  6022.3 1825.12  6043.9 1826.84  6052.8 1829.65  6063.0 1831.55  6124.0 1834.23
#Mann=3,-1,0
  4531.6    0.05       0  4994.0    0.03       0  5012.7    0.05       0
Bank Sta=4994,5012.7
Exp/Cntr=0.3,0.1

Type RM Length L Ch R = 1,5132,431,431,431
BEGIN DESCRIPTION:
Deadman 64 9.0
END DESCRIPTION:
XS GIS Cut Line= 3
      1635805.03      6866737.96      1635405.00      6867238.00
      1635199.77      6868206.64
#Sta/Elev= 30
  4360.0 1827.53  4445.7 1822.10  4495.3 1820.50  4609.0 1812.35  4673.0 1805.50
  4757.8 1803.33  4865.1 1805.04  4949.9 1805.05  4964.3 1803.76  4969.4 1799.26
  4969.9 1798.76  4988.1 1799.26  5010.6 1801.04  5031.0 1801.67  5041.2 1801.15
  5061.7 1802.16  5074.9 1801.13  5112.8 1803.14  5133.2 1802.60  5143.5 1799.79
  5153.7 1801.85  5169.1 1802.55  5276.4 1804.46  5593.2 1807.35  5655.7 1807.29
  5744.8 1809.26  5888.7 1810.46  5943.5 1812.09  5981.7 1814.63  5990.5 1814.42
#Mann=3,-1,0
  4360.0    0.05       0  4969.4    0.05       0  4988.1    0.05       0
Bank Sta=4969.4,4988.1
Exp/Cntr=0.3,0.1

Type RM Length L Ch R = 1,4701,531,531,531
BEGIN DESCRIPTION:
Mapping XS 159213a8
END DESCRIPTION:
XS GIS Cut Line= 3
      1635478.03      6866575.42      1635013.44      6867314.33
      1634817.76      6867883.50
#Sta/Elev= 30
  4102.9 1818.43  4187.9 1813.74  4266.8 1805.55  4294.9 1801.23  4309.3 1800.04
  4345.8 1800.03  4397.6 1801.81  4418.8 1801.23  4491.8 1802.57  4578.4 1802.63
  4607.2 1804.22  4680.2 1804.30  4816.9 1803.77  4926.4 1802.40  4941.7 1800.37
  4956.4 1799.58  5000.8 1799.86  5011.3 1798.79  5012.7 1797.59  5013.2 1797.09
  5031.6 1797.59  5053.6 1798.39  5064.2 1799.27  5074.0 1801.15  5079.3 1800.82
  5095.9 1802.74  5191.1 1802.94  5318.0 1805.94  5448.9 1814.83  5577.6 1816.39
#Mann=3,-1,0
  4102.9    0.05       0  5012.7    0.05       0  5031.6    0.05       0
Bank Sta=5012.7,5031.6
Exp/Cntr=0.3,0.1

Type RM Length L Ch R = 1,4170,486,486,486
BEGIN DESCRIPTION:
Deadman 64 8.0
END DESCRIPTION:
XS GIS Cut Line= 3
      1635403.96      6866456.93      1634555.00      6867138.00
      1634155.00      6867338.00
#Sta/Elev= 30
  3911.3 1815.93  3968.3 1812.62  4017.9 1811.00  4061.1 1806.94  4102.7 1799.88
  4117.1 1799.17  4139.5 1799.23  4153.6 1799.75  4166.7 1801.49  4209.9 1802.47
  4509.2 1801.49  4672.4 1802.43  4942.9 1800.14  4963.7 1799.27  4978.1 1796.54
  4998.6 1795.35  4999.1 1794.85  5017.1 1794.85  5017.6 1795.35  5022.0 1797.00
  5075.2 1798.46  5097.5 1800.25  5103.1 1801.51  5111.5 1801.60  5125.5 1803.08
  5259.6 1811.89  5290.4 1813.16  5312.7 1815.13  5379.8 1818.67  5446.9 1824.13
#Mann=3,-1,0
  3911.3    0.05       0  4998.6    0.05       0  5017.6    0.05       0
Bank Sta=4998.6,5017.6
Exp/Cntr=0.3,0.1

Type RM Length L Ch R = 1,3684,423,423,423
BEGIN DESCRIPTION:
Deadman 64 7.0
END DESCRIPTION:
XS GIS Cut Line= 3
      1635244.30      6866183.49      1634254.48      6866782.83
      1634005.03      6866937.98
#Sta/Elev= 30
  3842.3 1809.59  3960.7 1805.38  3976.2 1804.11  3997.6 1804.02  4018.9 1802.56
  4034.4 1800.12  4040.2 1800.58  4108.1 1797.83  4172.1 1800.51  4224.5 1800.85
  4340.8 1799.81  4414.3 1795.94  4426.2 1796.01  4457.2 1799.63  4478.5 1799.84
  4748.1 1796.83  4922.7 1798.76  4944.0 1797.42  4959.5 1795.38  4977.6 1791.25
  4978.1 1790.75  4996.6 1791.25  5017.6 1798.11  5038.8 1800.23  5054.2 1803.29
  5069.5 1804.21  5140.1 1812.12  5227.7 1818.23  5264.3 1823.19  5293.2 1825.80
#Mann=3,-1,0
  3842.3    0.05       0  4977.6    0.05       0  4996.6    0.05       0
Bank Sta=4977.6,4996.6
Exp/Cntr=0.3,0.1

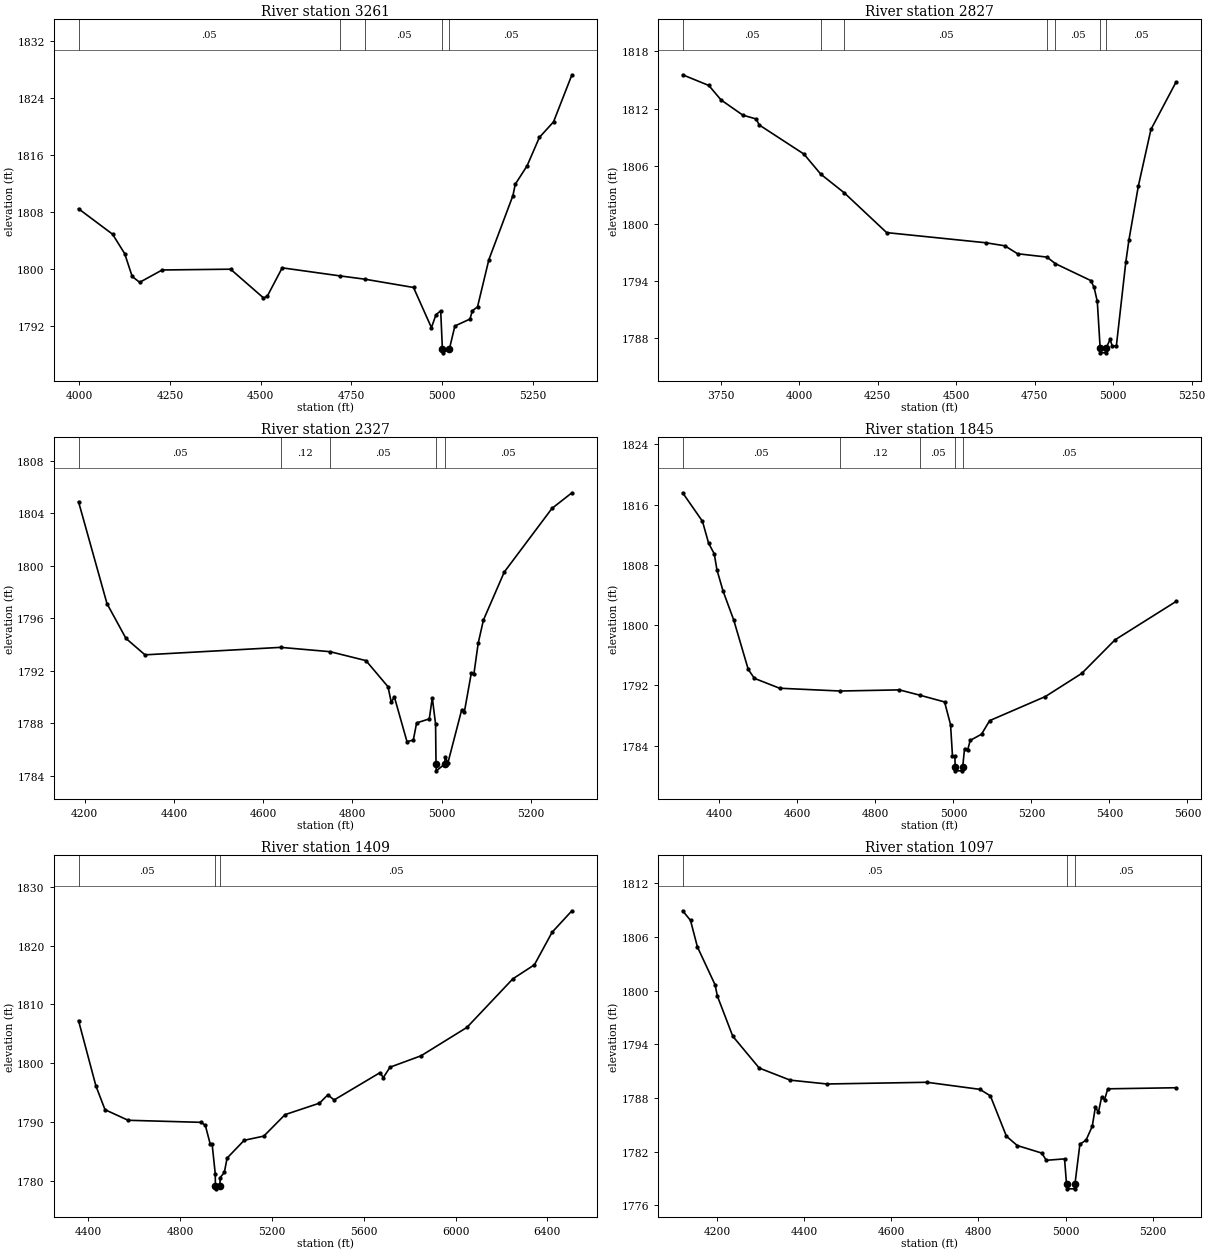
Type RM Length L Ch R = 1,3261,434,434,434
BEGIN DESCRIPTION:
Deadman 64 6.0
END DESCRIPTION:
XS GIS Cut Line= 3
      1635218.05      6866138.79      1634255.00      6866388.00
      1633904.98      6866488.01
#Sta/Elev= 30
  3998.4 1808.49  4092.2 1804.92  4125.5 1802.20  4146.2 1799.00  4166.8 1798.18
  4228.8 1799.91  4417.1 1800.02  4507.7 1796.00  4518.0 1796.21  4559.3 1800.21
  4717.2 1799.09  4786.9 1798.62  4920.9 1797.46  4970.3 1791.83  4982.8 1793.64
  4995.8 1794.19  5000.5 1788.80  5001.0 1788.30  5019.6 1788.80  5034.8 1792.06
  5076.4 1793.03  5082.9 1794.19  5097.2 1794.74  5128.4 1801.35  5194.7 1810.33
  5201.2 1811.93  5233.7 1814.50  5267.5 1818.48  5306.5 1820.66  5357.2 1827.26
#Mann=5,-1,0
  3998.4    0.05       0  4717.2    0.12       0  4786.9    0.05       0
  5000.5    0.05       0  5019.6    0.05       0
Bank Sta=5000.5,5019.6
Exp/Cntr=0.3,0.1

Type RM Length L Ch R = 1,2827,500,500,500
BEGIN DESCRIPTION:
Deadman 64 5.0
END DESCRIPTION:
XS GIS Cut Line= 3
      1635505.39      6865749.00      1634155.00      6865988.00
      1633954.97      6865988.00
#Sta/Elev= 30
  3628.7 1815.55  3712.2 1814.43  3751.0 1812.92  3820.4 1811.33  3862.7 1810.93
  3872.8 1810.30  4015.0 1807.26  4068.6 1805.16  4143.4 1803.21  4278.4 1799.05
  4593.9 1797.99  4654.8 1797.67  4695.4 1796.84  4789.1 1796.49  4816.0 1795.80
  4929.0 1794.03  4939.1 1793.32  4949.3 1791.85  4958.4 1786.98  4958.9 1786.48
  4977.0 1786.48  4977.5 1786.98  4989.9 1787.88  4997.5 1787.15  5010.1 1787.23
  5040.1 1795.97  5050.1 1798.29  5080.1 1803.93  5120.1 1809.83  5200.1 1814.79
#Mann=7,-1,0
  3628.7    0.05       0  4068.6    0.12       0  4143.4    0.05       0
  4789.1    0.12       0  4816.0    0.05       0  4958.4    0.05       0
  4977.5    0.05       0
Bank Sta=4958.4,4977.5
Exp/Cntr=0.3,0.1

Type RM Length L Ch R = 1,2327,482,482,482
BEGIN DESCRIPTION:
Deadman 64 4.0
END DESCRIPTION:
XS GIS Cut Line= 3
      1634754.98      6864938.02      1634155.00      6865488.00
      1633904.97      6865638.02
#Sta/Elev= 30
  4186.2 1804.88  4250.0 1797.11  4292.5 1794.46  4335.1 1793.21  4639.1 1793.78
  4749.9 1793.45  4830.2 1792.77  4879.6 1790.78  4887.0 1789.58  4893.7 1790.02
  4922.1 1786.60  4936.3 1786.71  4943.7 1788.02  4972.1 1788.33  4978.8 1789.94
  4986.2 1787.94  4987.2 1784.87  4987.7 1784.37  5006.3 1784.87  5007.9 1785.44
  5013.7 1784.96  5044.8 1789.03  5050.6 1788.84  5066.2 1791.81  5072.0 1791.73
  5081.7 1794.10  5093.4 1795.86  5140.1 1799.52  5247.0 1804.37  5291.7 1805.56
#Mann=5,-1,0
  4186.2    0.05       0  4639.1    0.12       0  4749.9    0.05       0
  4987.2    0.05       0  5006.3    0.05       0
Bank Sta=4987.2,5006.3
Exp/Cntr=0.3,0.1

Type RM Length L Ch R = 1,1845,436,436,436
BEGIN DESCRIPTION:
Deadman 64 3.0
END DESCRIPTION:
XS GIS Cut Line= 3
      1634754.97      6864688.02      1634155.00      6865038.00
      1633804.98      6865488.02
#Sta/Elev= 30
  4306.0 1817.56  4356.8 1813.78  4372.5 1810.88  4387.0 1809.46  4394.0 1807.32
  4409.7 1804.51  4437.0 1800.67  4474.2 1794.12  4490.0 1792.94  4554.5 1791.63
  4709.3 1791.26  4861.7 1791.41  4913.7 1790.71  4977.4 1789.81  4992.7 1786.80
  4997.7 1782.61  5003.8 1782.61  5004.6 1781.17  5005.1 1780.67  5023.3 1780.67
  5023.8 1781.17  5028.6 1783.62  5036.8 1783.48  5043.1 1784.71  5072.1 1785.53
  5092.9 1787.33  5235.9 1790.53  5329.1 1793.60  5414.1 1798.04  5570.7 1803.14
#Mann=5,-1,0
  4306.0    0.05       0  4709.3    0.12       0  4913.7    0.05       0
  5004.6    0.03       0  5023.8    0.05       0
Bank Sta=5004.6,5023.8
Exp/Cntr=0.3,0.1

Type RM Length L Ch R = 1,1409,312,312,312
BEGIN DESCRIPTION:
Deadman 64 2.0
END DESCRIPTION:
XS GIS Cut Line= 3
      1634555.02      6864437.99      1633955.00      6864688.00
      1633055.01      6865887.99
#Sta/Elev= 30
  4357.0 1807.25  4432.8 1796.14  4472.4 1792.11  4573.1 1790.31  4891.6 1789.96
  4909.5 1789.45  4931.2 1786.22  4939.3 1786.21  4952.8 1781.21  4953.5 1779.16
  4954.0 1778.66  4972.7 1779.16  4974.5 1780.58  4992.4 1781.45  5004.3 1783.88
  5078.9 1786.91  5164.3 1787.62  5257.0 1791.27  5407.0 1793.22  5443.5 1794.64
  5470.6 1793.76  5670.6 1798.40  5685.1 1797.56  5714.3 1799.33  5849.7 1801.27
  6049.7 1806.10  6249.7 1814.35  6343.5 1816.73  6420.6 1822.26  6507.0 1825.91
#Mann=3,-1,0
  4357.0    0.05       0  4953.5    0.05       0  4972.7    0.05       0
Bank Sta=4953.5,4972.7
Exp/Cntr=0.3,0.1

Type RM Length L Ch R = 1,1097,481,481,481
BEGIN DESCRIPTION:
Mapping XS 3b2365d8
END DESCRIPTION:
XS GIS Cut Line= 3
      1634568.51      6864380.22      1633724.76      6864516.94
      1633534.87      6864719.50
#Sta/Elev= 30
  4121.0 1808.94  4139.1 1807.86  4154.9 1804.90  4195.5 1800.66  4200.7 1799.41
  4236.0 1794.92  4296.8 1791.36  4367.7 1790.01  4452.4 1789.58  4681.7 1789.77
  4803.3 1788.98  4827.3 1788.25  4864.1 1783.74  4889.0 1782.70  4945.1 1781.86
  4955.7 1781.05  4997.5 1781.21  5002.1 1778.36  5002.6 1777.86  5020.8 1777.86
  5021.3 1778.36  5032.7 1782.84  5046.9 1783.31  5061.1 1784.85  5068.4 1787.03
  5075.2 1786.40  5082.5 1788.10  5089.4 1787.83  5096.7 1789.04  5253.4 1789.16
#Mann=3,-1,0
  4121.0    0.05       0  5002.1    0.05       0  5021.3    0.05       0
Bank Sta=5002.1,5021.3
Exp/Cntr=0.3,0.1

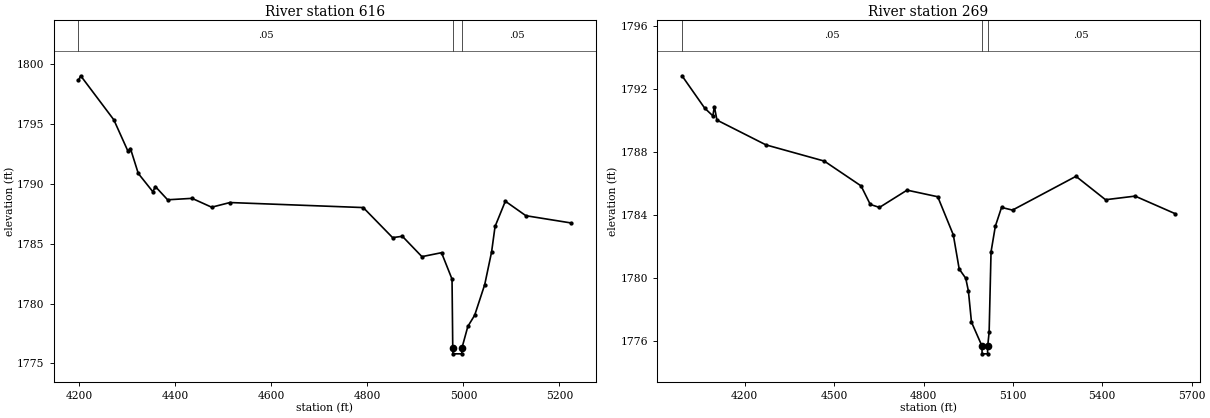
Type RM Length L Ch R = 1,616,347,347,347
BEGIN DESCRIPTION:
Mapping XS 437323a9
END DESCRIPTION:
XS GIS Cut Line= 3
      1634387.24      6863972.64      1633623.50      6864120.32
      1633433.63      6864280.66
#Sta/Elev= 30
  4198.4 1798.66  4203.0 1799.03  4272.0 1795.35  4301.5 1792.72  4306.6 1792.95
  4322.9 1790.87  4353.3 1789.34  4358.4 1789.78  4384.0 1788.67  4434.9 1788.79
  4475.7 1788.05  4513.8 1788.44  4791.4 1788.02  4852.5 1785.51  4872.9 1785.62
  4913.6 1783.92  4954.4 1784.25  4976.3 1782.04  4977.8 1776.30  4978.3 1775.80
  4996.5 1775.80  4997.0 1776.30  5009.2 1778.09  5023.5 1779.03  5044.4 1781.59
  5058.7 1784.32  5065.9 1786.44  5087.3 1788.55  5130.1 1787.34  5224.8 1786.73
#Mann=3,-1,0
  4198.4    0.05       0  4977.8    0.03       0  4997.0    0.05       0
Bank Sta=4977.8,4997
Exp/Cntr=0.3,0.1

Type RM Length L Ch R = 1,269,0,0,0
BEGIN DESCRIPTION:
Deadman 64 1.0
END DESCRIPTION:
XS GIS Cut Line= 3
      1634478.88      6863568.06      1633519.06      6863802.35
      1633103.69      6864323.46
#Sta/Elev= 30
  3989.3 1792.86  4065.4 1790.80  4092.8 1790.31  4097.9 1790.90  4106.5 1790.04
  4271.2 1788.46  4466.8 1787.43  4590.3 1785.85  4621.2 1784.67  4652.1 1784.48
  4744.7 1785.58  4847.7 1785.16  4900.0 1782.73  4919.7 1780.56  4941.7 1779.97
  4950.6 1779.16  4960.9 1777.18  4996.1 1775.66  4996.6 1775.16  5014.9 1775.16
  5015.4 1775.66  5020.2 1776.54  5026.6 1781.65  5041.0 1783.28  5061.8 1784.48
  5098.7 1784.31  5311.7 1786.46  5410.9 1784.97  5510.2 1785.20  5643.7 1784.09
#Mann=3,-1,0
  3989.3    0.05       0  4996.1    0.03       0  5015.4    0.05       0
Bank Sta=4996.1,5015.4
Exp/Cntr=0.3,0.1

Chan Stop Cuts=-1