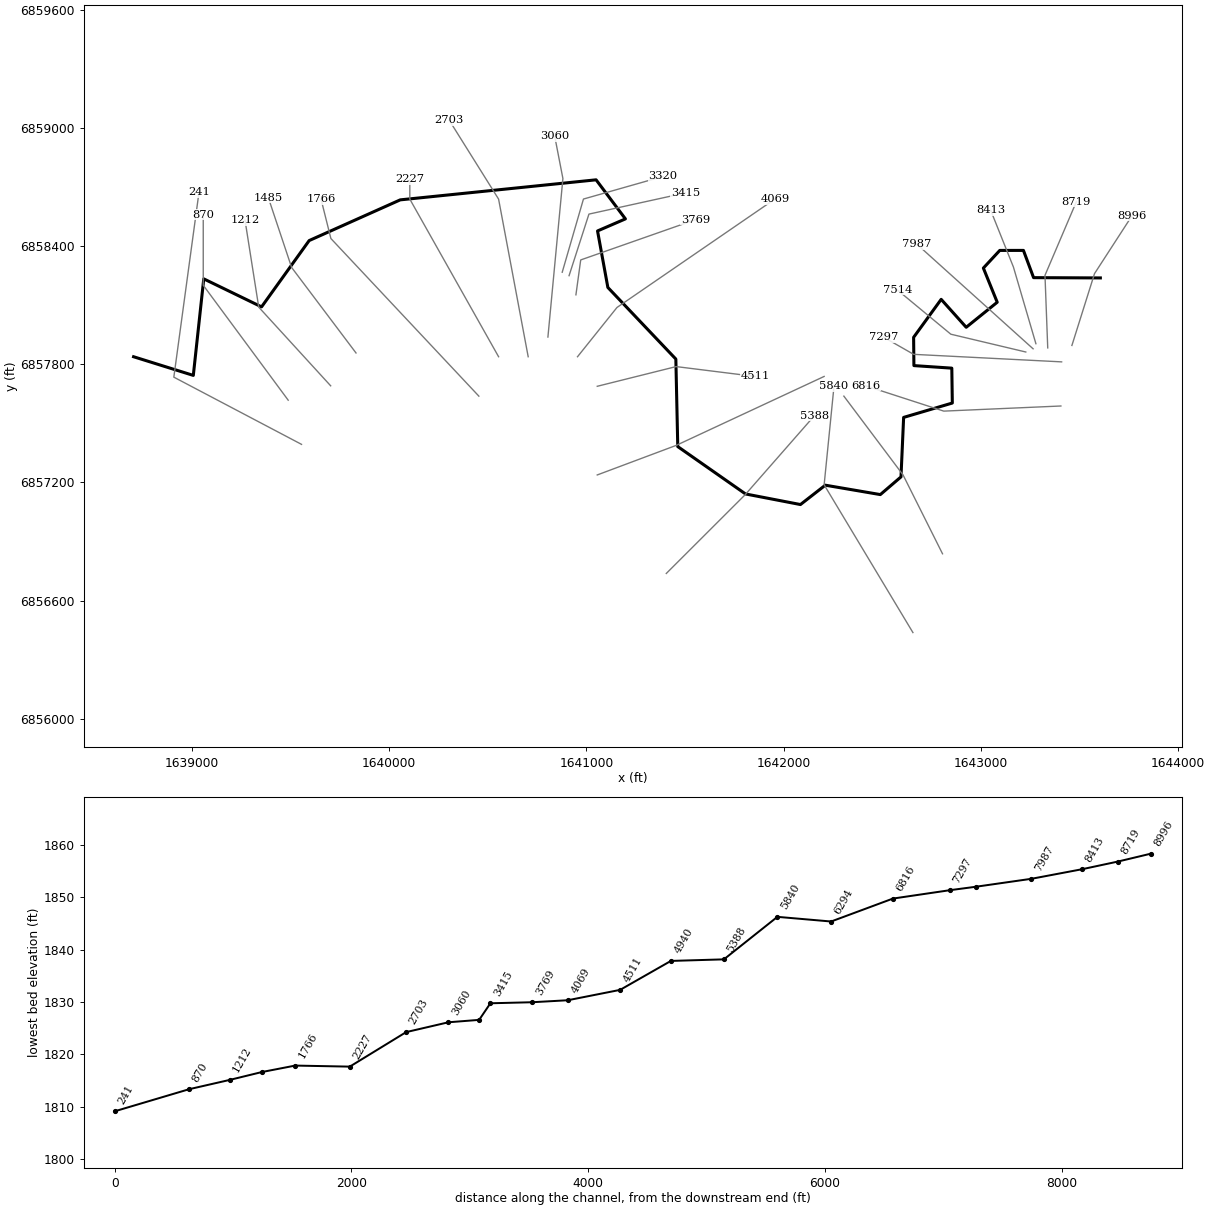
--- Deadman 65.prj (project) ---

Proj Title=Deadman 65 Base Level Engineering
Current Plan=p01
Default Exp/Contr=0.3,0.1
English Units
Geom File=g01
Flow File=f01
Plan File=p01
BEGIN DESCRIPTION:
Deadman 65
END DESCRIPTION:

--- Deadman 65.p01 (plan) ---

Plan Title=Multiple Run
Short Identifier=Multiple
Geom File=g01
Flow File=f01
Subcritical Flow
K Sum by GR= 0
Std Step Tol= 0.01
Critical Tol= 0.01
Num of Std Step Trials= 20
Max Error Tol= 0.3
Flow Tol Ratio= 0.001
Split Flow NTrial= 30
Split Flow Tol= 0.02
Split Flow Ratio= 0.02
Log Output Level= 0
Friction Slope Method= 1
Unsteady Friction Slope Method= 2
Unsteady Bridges Friction Slope Method= 1
Parabolic Critical Depth
Global Vel Dist=  1 , 1 , 1
Global Log Level= 0
CheckData=True
Encroach Param= -1, 0, 0, 0
BEGIN DESCRIPTION:
Multiple Run
END DESCRIPTION:

--- Deadman 65.f01 (steady flow) ---

Flow Title=Multiple
Number of Profiles=7
Profile Names=10-year,25-year,50-year,1pct_min,100-year,1pct_plu,500-year
River Rch & RM= Deadman 65,Reach-1,8996
     387     547     682     423     844    1683    1309
Boundary for River Rch & Prof#=Deadman 65,Reach-1,1
Up Type=0
Dn Type=3
Dn Slope=0.005
Boundary for River Rch & Prof#=Deadman 65,Reach-1,2
Up Type=0
Dn Type=3
Dn Slope=0.005
Boundary for River Rch & Prof#=Deadman 65,Reach-1,3
Up Type=0
Dn Type=3
Dn Slope=0.005
Boundary for River Rch & Prof#=Deadman 65,Reach-1,4
Up Type=0
Dn Type=3
Dn Slope=0.005
Boundary for River Rch & Prof#=Deadman 65,Reach-1,5
Up Type=0
Dn Type=3
Dn Slope=0.005
Boundary for River Rch & Prof#=Deadman 65,Reach-1,6
Up Type=0
Dn Type=3
Dn Slope=0.005
Boundary for River Rch & Prof#=Deadman 65,Reach-1,7
Up Type=0
Dn Type=3
Dn Slope=0.005

--- Deadman 65.g01 (geometry) ---

Geom Title=Existing Conditions

River Reach=Deadman 65,Reach-1
Reach XY= 30
      1643605.00      6858238.00      1643266.58      6858239.39
      1643215.15      6858377.72      1643095.17      6858377.57
      1643012.08      6858288.02      1643082.30      6858114.53
      1642925.06      6857987.48      1642798.20      6858129.23
      1642658.54      6857936.52      1642659.99      6857793.00
      1642852.09      6857780.09      1642854.68      6857603.02
      1642607.91      6857530.09      1642594.53      6857228.17
      1642489.84      6857138.36      1642210.89      6857186.03
      1642084.95      6857087.79      1641806.47      6857141.56
      1641463.14      6857381.94      1641453.39      6857826.17
      1641108.82      6858189.58      1641056.49      6858476.46
      1641197.81      6858537.67      1641049.16      6858735.95
      1640056.56      6858634.24      1639594.90      6858427.61
      1639353.58      6858091.04      1639060.59      6858233.27
      1639007.71      6857743.28      1638705.00      6857838.00

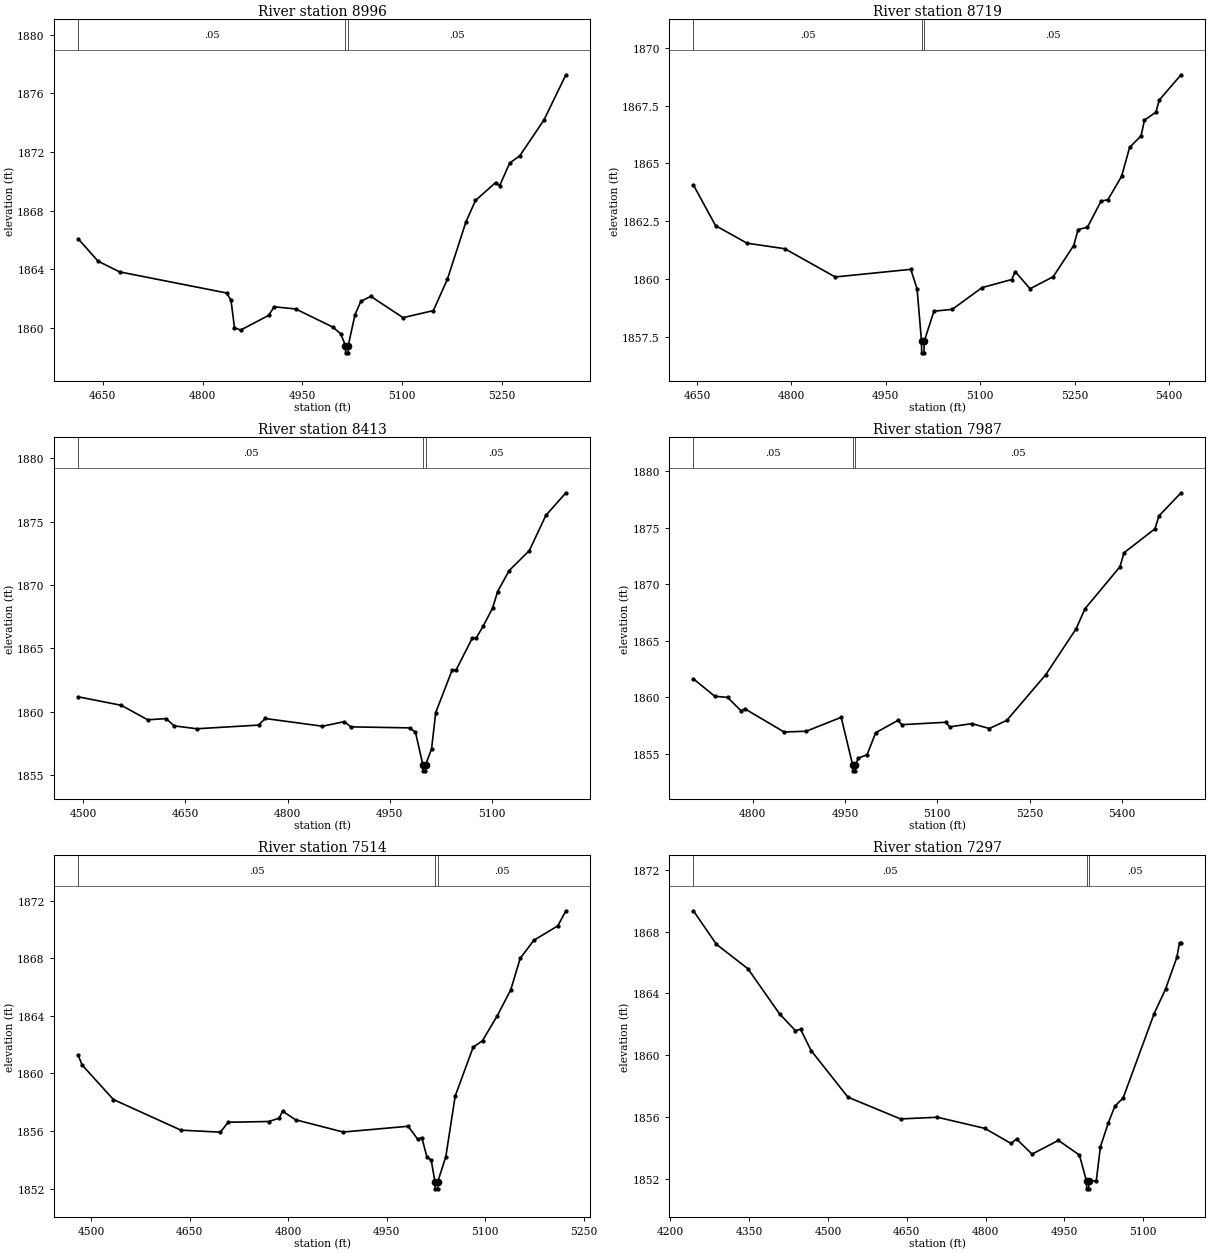
Type RM Length L Ch R = 1,8996,277,277,277
BEGIN DESCRIPTION:
Deadman 65 14.0
END DESCRIPTION:
XS GIS Cut Line= 3
      1643460.82      6857895.29      1643575.40      6858259.87
      1643765.72      6858554.00
#Sta/Elev= 30
  4613.3 1866.08  4643.1 1864.56  4675.5 1863.83  4836.3 1862.39  4842.8 1861.88
  4848.0 1860.03  4857.2 1859.86  4899.2 1860.86  4907.6 1861.45  4940.0 1861.30
  4995.5 1860.07  5007.5 1859.61  5014.6 1858.81  5014.9 1858.31  5018.6 1858.31
  5018.9 1858.81  5029.0 1860.91  5037.8 1861.82  5052.8 1862.16  5101.2 1860.71
  5146.7 1861.19  5167.8 1863.33  5195.7 1867.24  5210.0 1868.70  5240.3 1869.92
  5246.3 1869.71  5261.4 1871.25  5276.6 1871.75  5312.9 1874.19  5345.8 1877.27
#Mann=3,-1,0
  4613.3    0.05       0  5014.6    0.03       0  5018.9    0.05       0
Bank Sta=5014.6,5018.9
Exp/Cntr=0.3,0.1

Type RM Length L Ch R = 1,8719,306,306,306
BEGIN DESCRIPTION:
Mapping XS d430ff22
END DESCRIPTION:
XS GIS Cut Line= 3
      1643338.27      6857882.87      1643324.36      6858251.29
      1643483.46      6858624.83
#Sta/Elev= 30
  4644.4 1864.07  4679.6 1862.31  4729.6 1861.55  4789.6 1861.31  4869.7 1860.09
  4989.8 1860.42  4999.8 1859.57  5006.8 1857.31  5007.1 1856.81  5010.8 1856.81
  5011.1 1857.31  5026.6 1858.61  5055.7 1858.69  5103.0 1859.63  5150.2 1859.98
  5155.7 1860.32  5179.3 1859.58  5216.0 1860.10  5248.6 1861.45  5255.6 1862.14
  5270.4 1862.24  5292.1 1863.37  5302.9 1863.43  5324.7 1864.44  5337.4 1865.69
  5355.6 1866.19  5361.0 1866.87  5379.1 1867.21  5384.6 1867.74  5419.1 1868.83
#Mann=3,-1,0
  4644.4    0.05       0  5006.8    0.05       0  5011.1    0.05       0
Bank Sta=5006.8,5011.1
Exp/Cntr=0.3,0.1

Type RM Length L Ch R = 1,8413,426,426,426
BEGIN DESCRIPTION:
Mapping XS b152d870
END DESCRIPTION:
XS GIS Cut Line= 4
      1643278.29      6857904.19      1643247.90      6858008.01
      1643164.49      6858293.00      1643049.33      6858580.90
#Sta/Elev= 30
  4493.0 1861.17  4556.2 1860.50  4594.8 1859.36  4622.0 1859.45  4633.5 1858.88
  4666.9 1858.65  4757.5 1858.94  4767.2 1859.46  4851.2 1858.85  4883.1 1859.21
  4892.9 1858.80  4978.9 1858.72  4987.6 1858.38  4998.3 1855.83  4998.5 1855.33
  5002.3 1855.33  5002.6 1855.83  5011.2 1857.06  5017.3 1859.93  5041.5 1863.30
  5046.9 1863.26  5071.1 1865.82  5076.5 1865.80  5086.6 1866.72  5100.7 1868.17
  5108.1 1869.48  5125.0 1871.13  5154.6 1872.71  5178.8 1875.48  5208.2 1877.27
#Mann=3,-1,0
  4493.0    0.05       0  4998.3    0.05       0  5002.6    0.05       0
Bank Sta=4998.3,5002.6
Exp/Cntr=0.3,0.1

Type RM Length L Ch R = 1,7987,473,473,473
BEGIN DESCRIPTION:
Mapping XS c073aaab
END DESCRIPTION:
XS GIS Cut Line= 2
      1643264.10      6857878.27      1642675.57      6858408.87
#Sta/Elev= 30
  4703.7 1861.64  4738.4 1860.10  4759.3 1860.00  4781.0 1858.82  4787.7 1858.98
  4851.2 1856.94  4887.1 1857.01  4943.9 1858.24  4962.6 1854.01  4962.9 1853.51
  4966.7 1853.51  4967.0 1854.01  4971.8 1854.64  4985.8 1854.92  5000.0 1856.88
  5035.8 1857.96  5042.6 1857.59  5113.6 1857.80  5120.3 1857.40  5156.2 1857.68
  5184.6 1857.25  5213.0 1857.97  5276.5 1862.02  5325.8 1866.08  5340.0 1867.83
  5396.8 1871.54  5403.5 1872.78  5453.6 1874.89  5460.3 1876.04  5496.1 1878.08
#Mann=3,-1,0
  4703.7    0.05       0  4962.6    0.05       0  4967.0    0.05       0
Bank Sta=4962.6,4967
Exp/Cntr=0.3,0.1

Type RM Length L Ch R = 1,7514,217,217,217
BEGIN DESCRIPTION:
Mapping XS 7f1c75ac
END DESCRIPTION:
XS GIS Cut Line= 3
      1643227.06      6857862.03      1642847.06      6857952.40
      1642576.00      6858177.12
#Sta/Elev= 30
  4480.2 1861.27  4485.9 1860.60  4533.7 1858.19  4636.5 1856.06  4696.8 1855.92
  4708.5 1856.61  4770.1 1856.66  4786.2 1856.89  4791.4 1857.38  4811.2 1856.78
  4883.7 1855.93  4982.7 1856.33  4997.0 1855.44  5003.5 1855.54  5011.3 1854.18
  5017.8 1853.98  5023.4 1852.48  5023.7 1851.98  5027.5 1851.98  5027.8 1852.48
  5040.0 1854.21  5054.3 1858.43  5081.6 1861.82  5095.9 1862.28  5118.1 1863.99
  5138.9 1865.81  5153.3 1868.00  5174.1 1869.26  5210.6 1870.26  5222.9 1871.31
#Mann=3,-1,0
  4480.2    0.05       0  5023.4    0.05       0  5027.8    0.05       0
Bank Sta=5023.4,5027.8
Exp/Cntr=0.3,0.1

Type RM Length L Ch R = 1,7297,481,481,481
BEGIN DESCRIPTION:
Deadman 65 13.0
END DESCRIPTION:
XS GIS Cut Line= 3
      1643408.77      6857811.95      1642658.73      6857850.15
      1642504.98      6857938.01
#Sta/Elev= 30
  4244.0 1869.35  4287.8 1867.18  4347.9 1865.59  4408.0 1862.67  4438.0 1861.59
  4448.0 1861.67  4468.1 1860.29  4538.2 1857.27  4638.3 1855.86  4708.4 1855.97
  4798.5 1855.25  4848.6 1854.27  4859.0 1854.56  4888.6 1853.58  4938.7 1854.47
  4978.7 1853.52  4992.2 1851.83  4992.5 1851.33  4996.3 1851.33  4996.6 1851.83
  5010.8 1851.85  5018.7 1854.06  5033.9 1855.62  5046.1 1856.68  5061.9 1857.22
  5121.0 1862.69  5142.6 1864.27  5164.2 1866.34  5169.2 1867.28  5172.1 1867.28
#Mann=3,-1,0
  4244.0    0.05       0  4992.2    0.05       0  4996.6    0.05       0
Bank Sta=4992.2,4996.6
Exp/Cntr=0.3,0.1

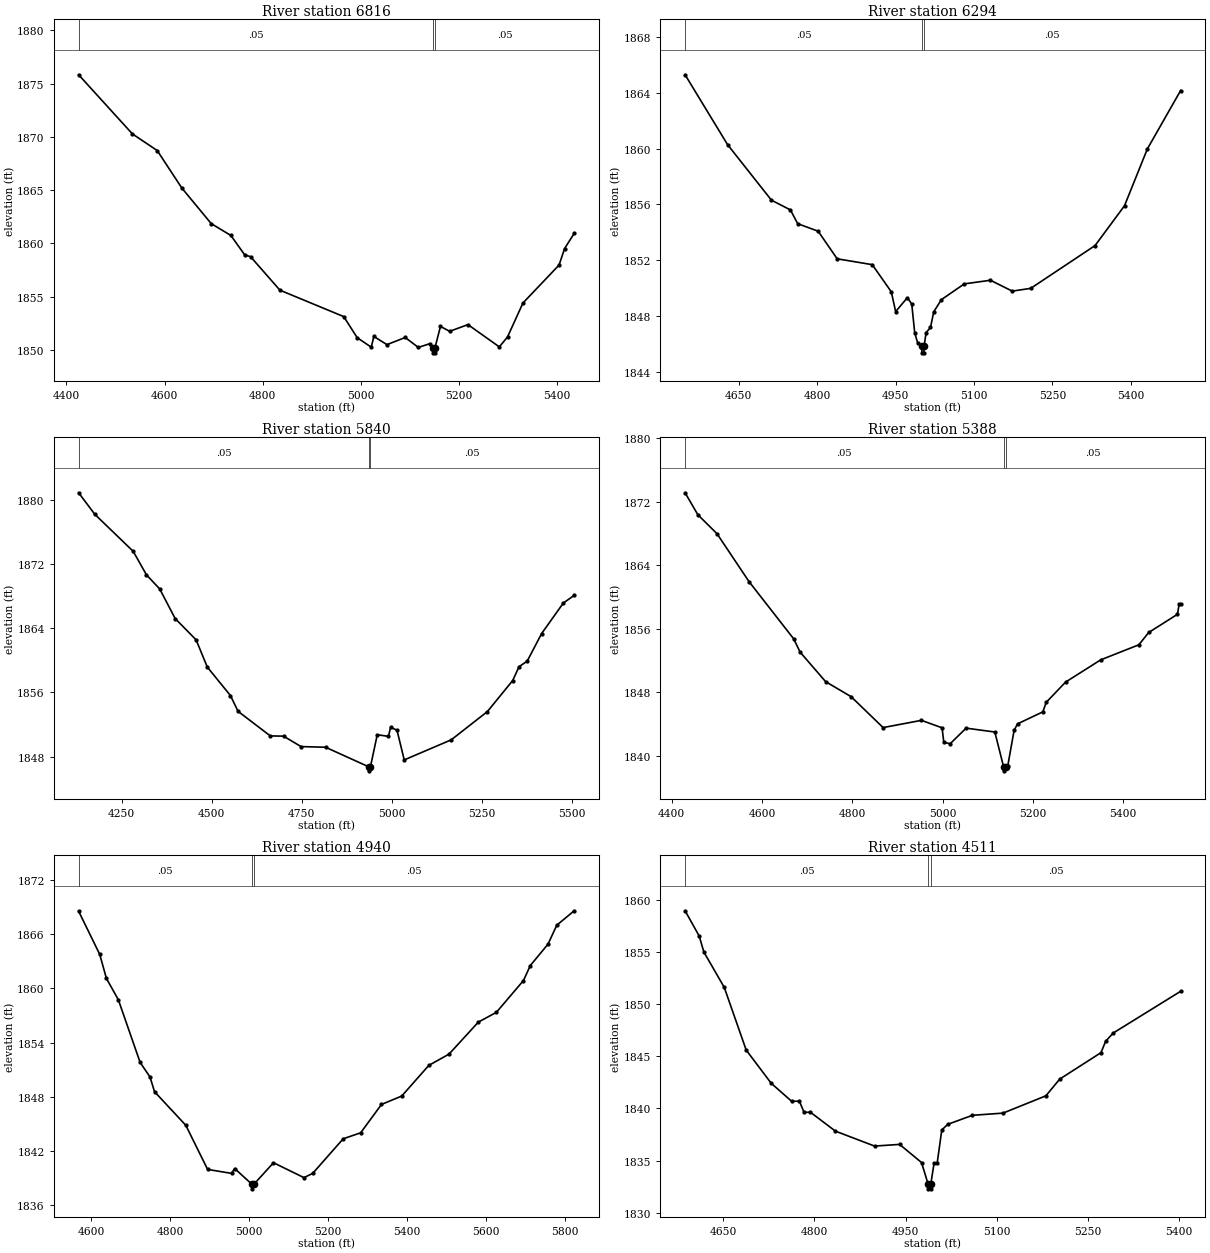
Type RM Length L Ch R = 1,6816,522,522,522
BEGIN DESCRIPTION:
Deadman 65 12.0
END DESCRIPTION:
XS GIS Cut Line= 3
      1643405.02      6857588.00      1642811.51      6857561.96
      1642415.72      6857690.42
#Sta/Elev= 30
  4424.8 1875.83  4534.4 1870.28  4585.0 1868.72  4635.0 1865.21  4695.1 1861.86
  4735.1 1860.75  4763.6 1858.91  4775.2 1858.76  4835.2 1855.61  4965.3 1853.13
  4992.7 1851.15  5021.4 1850.26  5026.6 1851.27  5053.3 1850.50  5090.6 1851.17
  5117.3 1850.24  5141.4 1850.60  5147.0 1850.23  5147.3 1849.73  5151.1 1849.73
  5151.4 1850.23  5162.4 1852.21  5181.2 1851.75  5218.4 1852.38  5282.4 1850.29
  5299.1 1851.22  5330.6 1854.41  5404.2 1857.97  5415.5 1859.52  5435.0 1860.94
#Mann=3,-1,0
  4424.8    0.05       0  5147.0    0.03       0  5151.4    0.05       0
Bank Sta=5147,5151.4
Exp/Cntr=0.3,0.1

Type RM Length L Ch R = 1,6294,454,454,454
BEGIN DESCRIPTION:
Deadman 65 11.0
END DESCRIPTION:
XS GIS Cut Line= 3
      1642805.02      6856837.96      1642605.00      6857238.00
      1642304.98      6857638.03
#Sta/Elev= 30
  4547.7 1865.31  4628.8 1860.30  4712.7 1856.31  4749.0 1855.61  4763.0 1854.62
  4802.1 1854.08  4838.4 1852.10  4905.5 1851.68  4941.9 1849.73  4950.2 1848.31
  4972.6 1849.31  4981.0 1848.85  4986.6 1846.80  4992.2 1846.07  5000.0 1845.85
  5000.3 1845.35  5004.2 1845.35  5004.6 1845.85  5008.5 1846.81  5016.8 1847.17
  5023.1 1848.30  5037.7 1849.17  5081.4 1850.30  5131.4 1850.56  5173.1 1849.78
  5208.5 1849.98  5331.4 1853.05  5387.7 1855.91  5431.4 1859.99  5495.0 1864.18
#Mann=3,-1,0
  4547.7    0.05       0  5000.0    0.05       0  5004.6    0.05       0
Bank Sta=5000,5004.6
Exp/Cntr=0.3,0.1

Type RM Length L Ch R = 1,5840,452,452,452
BEGIN DESCRIPTION:
Deadman 65 10.0
END DESCRIPTION:
XS GIS Cut Line= 3
      1642655.00      6856438.00      1642205.00      6857188.00
      1642255.00      6857687.97
#Sta/Elev= 30
  4130.2 1880.87  4174.9 1878.20  4281.8 1873.58  4318.7 1870.65  4355.7 1868.88
  4398.4 1865.21  4456.7 1862.55  4487.8 1859.16  4552.0 1855.62  4573.3 1853.65
  4662.8 1850.59  4699.7 1850.56  4748.3 1849.26  4816.3 1849.18  4936.5 1846.74
  4936.8 1846.24  4941.1 1846.74  4960.1 1850.74  4991.2 1850.53  4997.1 1851.65
  5014.9 1851.31  5035.0 1847.60  5165.6 1850.10  5266.1 1853.62  5336.5 1857.49
  5354.1 1859.21  5376.7 1859.90  5416.9 1863.34  5477.2 1867.14  5507.3 1868.09
#Mann=3,-1,0
  4130.2    0.05       0  4936.5    0.05       0  4941.1    0.05       0
Bank Sta=4936.5,4941.1
Exp/Cntr=0.3,0.1

Type RM Length L Ch R = 1,5388,448,448,448
BEGIN DESCRIPTION:
Deadman 65 9.0
END DESCRIPTION:
XS GIS Cut Line= 3
      1641405.00      6856738.00      1641805.00      6857138.00
      1642155.00      6857538.00
#Sta/Elev= 30
  4429.9 1873.15  4458.2 1870.38  4500.6 1867.99  4571.3 1861.97  4670.3 1854.75
  4684.5 1853.08  4741.0 1849.36  4797.6 1847.46  4868.3 1843.57  4953.2 1844.48
  4998.9 1843.54  5002.7 1841.71  5016.9 1841.54  5052.1 1843.50  5115.7 1843.01
  5135.1 1838.62  5135.5 1838.12  5139.8 1838.62  5144.1 1838.68  5158.4 1843.23
  5166.0 1844.04  5222.0 1845.55  5229.5 1846.75  5272.3 1849.30  5350.1 1852.10
  5434.6 1854.00  5456.4 1855.55  5520.0 1857.84  5523.8 1859.11  5527.1 1859.11
#Mann=3,-1,0
  4429.9    0.05       0  5135.1    0.05       0  5139.8    0.05       0
Bank Sta=5135.1,5139.8
Exp/Cntr=0.3,0.1

Type RM Length L Ch R = 1,4940,429,429,429
BEGIN DESCRIPTION:
Deadman 65 8.0
END DESCRIPTION:
XS GIS Cut Line= 3
      1641055.01      6857238.00      1641455.00      6857388.00
      1642204.97      6857737.99
#Sta/Elev= 30
  4568.0 1868.54  4621.4 1863.77  4638.3 1861.11  4668.6 1858.74  4723.7 1851.81
  4748.7 1850.20  4760.2 1848.57  4839.4 1844.85  4894.6 1839.97  4955.1 1839.53
  4963.1 1840.07  5007.0 1838.32  5007.3 1837.82  5011.7 1838.32  5061.4 1840.71
  5138.6 1839.06  5160.7 1839.53  5238.0 1843.36  5282.1 1844.02  5334.9 1847.16
  5386.2 1848.09  5454.7 1851.48  5506.0 1852.73  5580.1 1856.27  5625.8 1857.35
  5694.4 1860.87  5711.7 1862.53  5756.6 1864.90  5778.7 1866.99  5822.8 1868.59
#Mann=3,-1,0
  4568.0    0.05       0  5007.0    0.05       0  5011.7    0.05       0
Bank Sta=5007,5011.7
Exp/Cntr=0.3,0.1

Type RM Length L Ch R = 1,4511,442,442,442
BEGIN DESCRIPTION:
Deadman 65 7.0
END DESCRIPTION:
XS GIS Cut Line= 3
      1641055.02      6857688.00      1641455.00      6857788.00
      1641855.00      6857738.00
#Sta/Elev= 30
  4587.2 1858.95  4610.4 1856.53  4618.1 1854.99  4651.6 1851.61  4687.7 1845.60
  4728.9 1842.41  4762.4 1840.69  4775.3 1840.69  4783.0 1839.62  4793.3 1839.64
  4834.6 1837.82  4899.0 1836.39  4940.2 1836.55  4976.3 1834.81  4986.8 1832.79
  4987.1 1832.29  4991.2 1832.29  4991.6 1832.79  4996.9 1834.76  5002.0 1834.76
  5009.6 1837.94  5019.6 1838.48  5060.0 1839.34  5110.3 1839.55  5180.9 1841.21
  5203.6 1842.81  5271.6 1845.35  5279.2 1846.44  5291.7 1847.23  5402.6 1851.23
#Mann=3,-1,0
  4587.2    0.05       0  4986.8    0.05       0  4991.6    0.05       0
Bank Sta=4986.8,4991.6
Exp/Cntr=0.3,0.1

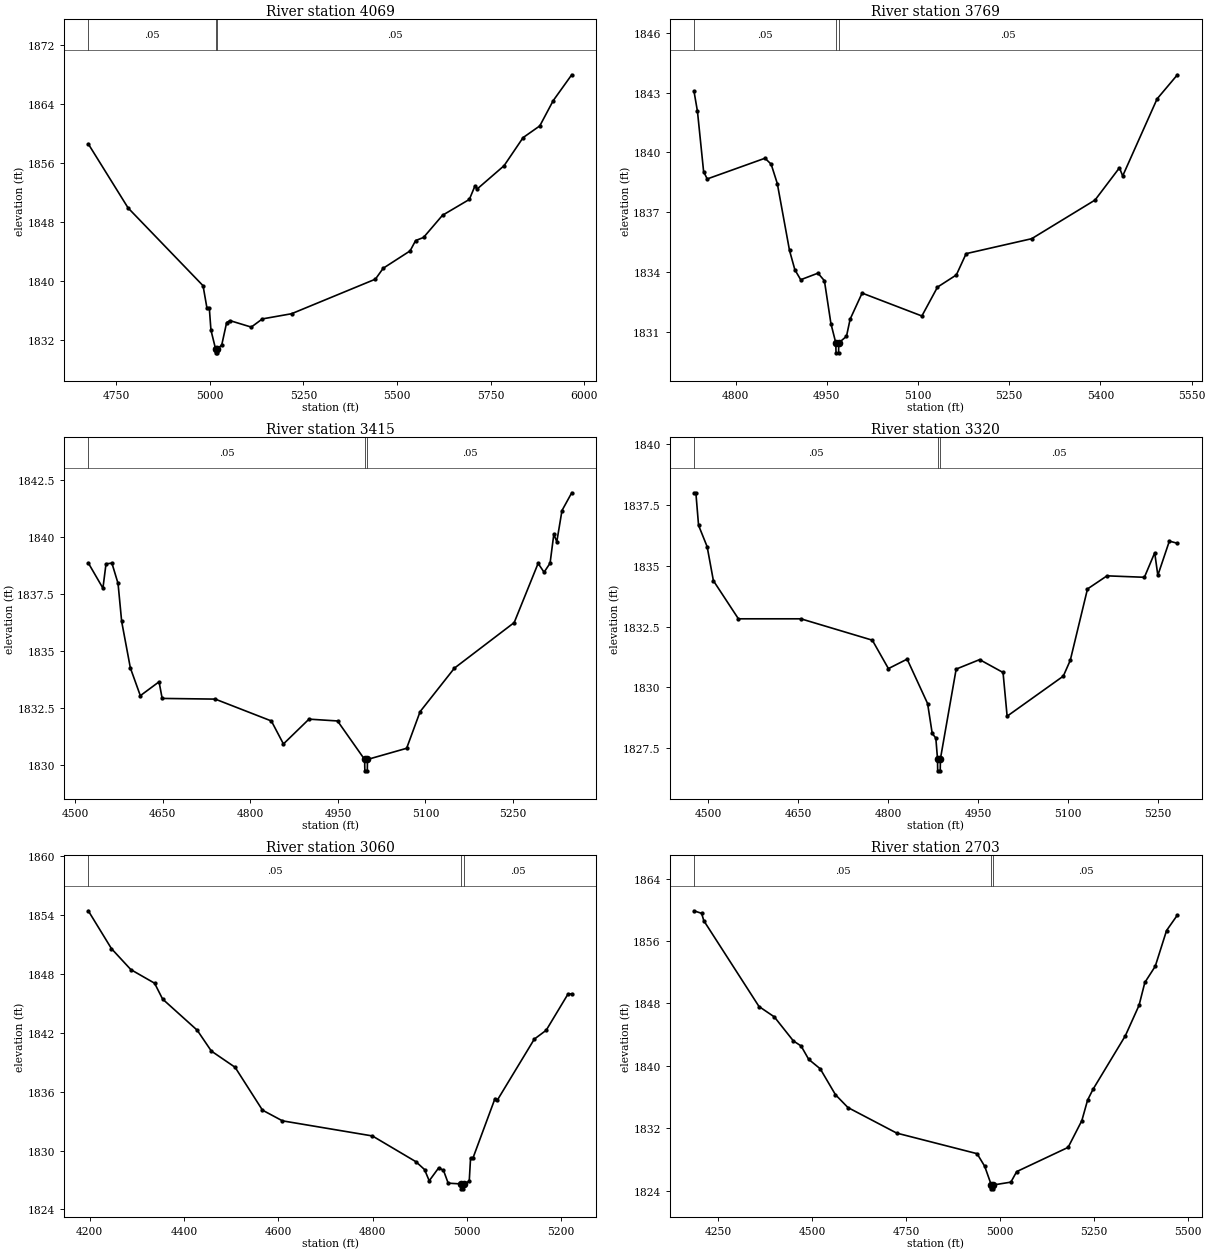
Type RM Length L Ch R = 1,4069,300,300,300
BEGIN DESCRIPTION:
Deadman 65 6.0
END DESCRIPTION:
XS GIS Cut Line= 3
      1640955.01      6857838.01      1641155.00      6858088.00
      1641955.03      6858638.02
#Sta/Elev= 30
  4675.3 1858.64  4781.7 1849.95  4981.8 1839.41  4992.2 1836.38  4998.5 1836.38
  5002.9 1833.38  5015.4 1830.81  5015.7 1830.31  5019.8 1830.31  5020.2 1830.81
  5031.8 1831.40  5044.8 1834.42  5053.6 1834.68  5110.5 1833.80  5140.2 1834.91
  5218.0 1835.61  5442.0 1840.30  5462.9 1841.78  5534.6 1844.13  5549.5 1845.54
  5570.5 1845.95  5621.2 1848.96  5692.9 1851.11  5707.8 1852.93  5713.9 1852.53
  5785.6 1855.68  5836.4 1859.49  5881.0 1861.08  5916.9 1864.51  5966.3 1868.01
#Mann=3,-1,0
  4675.3    0.05       0  5015.4    0.05       0  5020.2    0.05       0
Bank Sta=5015.4,5020.2
Exp/Cntr=0.3,0.1

Type RM Length L Ch R = 1,3769,354,354,354
BEGIN DESCRIPTION:
Mapping XS 922e6895
END DESCRIPTION:
XS GIS Cut Line= 3
      1640946.93      6858152.21      1640971.23      6858329.32
      1641552.84      6858533.57
#Sta/Elev= 30
  4731.4 1843.08  4737.2 1842.05  4747.3 1839.03  4753.2 1838.66  4848.3 1839.70
  4858.4 1839.40  4868.5 1838.43  4888.6 1835.07  4897.4 1834.10  4907.0 1833.60
  4935.4 1833.93  4946.0 1833.55  4956.7 1831.40  4964.7 1830.43  4965.1 1829.93
  4969.3 1829.93  4969.6 1830.43  4982.3 1830.76  4988.3 1831.62  5008.0 1832.93
  5106.3 1831.78  5132.0 1833.23  5163.0 1833.84  5179.1 1834.91  5286.9 1835.66
  5391.1 1837.60  5431.3 1839.22  5436.6 1838.81  5493.2 1842.68  5526.6 1843.89
#Mann=3,-1,0
  4731.4    0.05       0  4964.7    0.05       0  4969.6    0.05       0
Bank Sta=4964.7,4969.6
Exp/Cntr=0.3,0.1

Type RM Length L Ch R = 1,3415,95,95,95
BEGIN DESCRIPTION:
Mapping XS 33041fdd
END DESCRIPTION:
XS GIS Cut Line= 3
      1640912.19      6858249.42      1641012.90      6858561.96
      1641501.27      6858669.33
#Sta/Elev= 30
  4522.3 1838.86  4547.4 1837.75  4552.7 1838.82  4562.8 1838.85  4573.3 1837.96
  4579.5 1836.29  4594.4 1834.25  4611.5 1833.03  4643.6 1833.64  4648.9 1832.91
  4739.8 1832.88  4836.0 1831.92  4856.7 1830.91  4900.5 1832.00  4949.4 1831.92
  4995.8 1830.23  4996.2 1829.73  5000.4 1829.73  5000.7 1830.23  5067.8 1830.72
  5090.9 1832.33  5149.7 1834.24  5252.1 1836.24  5293.1 1838.84  5303.3 1838.45
  5313.6 1838.85  5320.0 1840.12  5325.1 1839.79  5334.0 1841.16  5350.7 1841.94
#Mann=3,-1,0
  4522.3    0.05       0  4995.8    0.05       0  5000.7    0.05       0
Bank Sta=4995.8,5000.7
Exp/Cntr=0.3,0.1

Type RM Length L Ch R = 1,3320,260,260,260
BEGIN DESCRIPTION:
Mapping XS 72e43845
END DESCRIPTION:
XS GIS Cut Line= 3
      1640877.49      6858266.84      1640985.12      6858638.35
      1641387.86      6858752.92
#Sta/Elev= 30
  4476.4 1838.01  4479.6 1838.01  4484.1 1836.67  4498.4 1835.79  4508.8 1834.39
  4550.5 1832.82  4654.6 1832.82  4773.6 1831.94  4800.4 1830.77  4831.6 1831.16
  4865.7 1829.33  4873.4 1828.10  4879.4 1827.91  4882.2 1827.06  4882.5 1826.56
  4886.7 1826.56  4887.1 1827.06  4913.3 1830.75  4952.4 1831.14  4991.4 1830.61
  4998.2 1828.81  5091.8 1830.46  5103.4 1831.11  5132.1 1834.05  5164.6 1834.59
  5226.9 1834.53  5244.1 1835.54  5249.3 1834.61  5268.5 1836.02  5281.9 1835.93
#Mann=3,-1,0
  4476.4    0.05       0  4882.2    0.03       0  4887.1    0.05       0
Bank Sta=4882.2,4887.1
Exp/Cntr=0.3,0.1

Type RM Length L Ch R = 1,3060,357,357,357
BEGIN DESCRIPTION:
Deadman 65 5.0
END DESCRIPTION:
XS GIS Cut Line= 3
      1640805.00      6857937.97      1640880.96      6858742.51
      1640839.65      6858955.93
#Sta/Elev= 30
  4197.1 1854.44  4246.3 1850.58  4287.5 1848.44  4337.7 1847.06  4354.8 1845.44
  4428.1 1842.27  4458.2 1840.14  4508.5 1838.49  4566.6 1834.12  4609.0 1833.03
  4799.8 1831.49  4891.9 1828.87  4910.3 1828.07  4920.3 1826.92  4940.4 1828.24
  4950.5 1827.99  4960.5 1826.68  4987.5 1826.60  4988.0 1826.10  4992.7 1826.10
  4993.2 1826.60  5005.2 1826.88  5008.0 1829.25  5013.1 1829.24  5059.8 1835.30
  5064.9 1835.15  5143.2 1841.36  5168.4 1842.26  5214.5 1845.94  5222.6 1845.98
#Mann=3,-1,0
  4197.1    0.05       0  4987.5    0.03       0  4993.2    0.05       0
Bank Sta=4987.5,4993.2
Exp/Cntr=0.3,0.1

Type RM Length L Ch R = 1,2703,476,476,476
BEGIN DESCRIPTION:
Deadman 65 4.0
END DESCRIPTION:
XS GIS Cut Line= 3
      1640705.00      6857838.00      1640555.00      6858638.00
      1640305.02      6859037.96
#Sta/Elev= 30
  4185.6 1859.89  4206.0 1859.56  4211.9 1858.61  4358.6 1847.61  4399.3 1846.28
  4450.1 1843.19  4470.5 1842.55  4490.8 1840.83  4521.4 1839.62  4562.0 1836.29
  4595.1 1834.65  4724.8 1831.37  4938.5 1828.73  4958.8 1827.11  4976.3 1824.72
  4976.8 1824.22  4981.6 1824.22  4982.0 1824.72  5028.4 1825.08  5043.8 1826.43
  5180.6 1829.54  5217.1 1832.97  5232.4 1835.61  5247.2 1837.02  5332.7 1843.85
  5369.2 1847.76  5384.6 1850.69  5412.3 1852.77  5442.4 1857.36  5471.2 1859.34
#Mann=3,-1,0
  4185.6    0.05       0  4976.3    0.05       0  4982.0    0.05       0
Bank Sta=4976.3,4982
Exp/Cntr=0.3,0.1

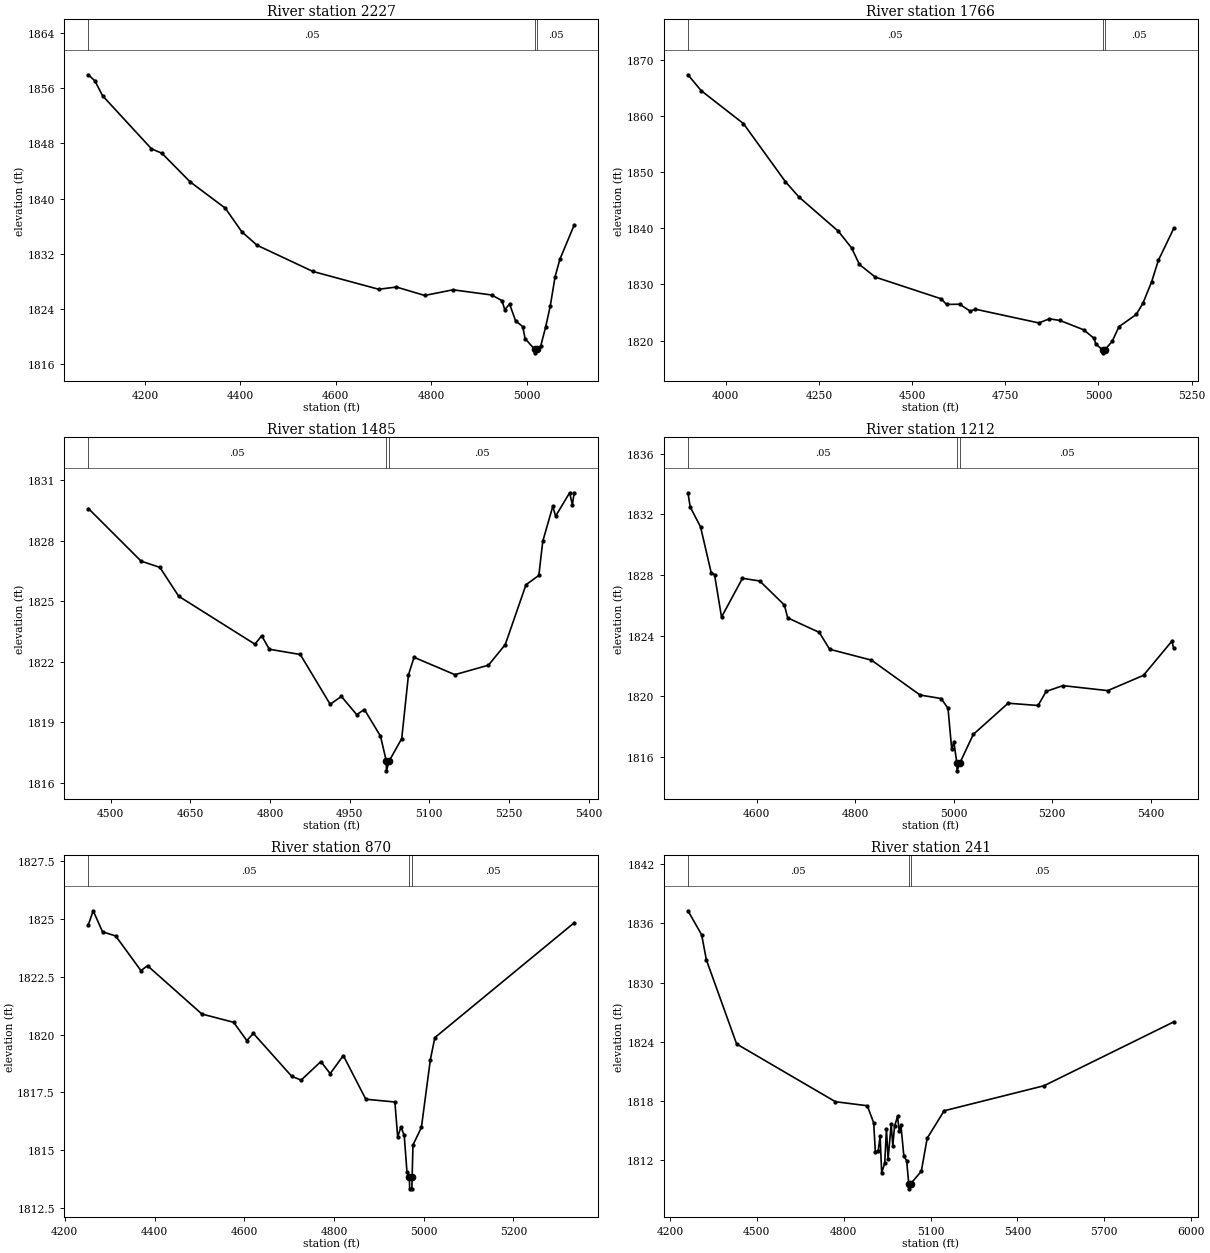
Type RM Length L Ch R = 1,2227,461,461,461
BEGIN DESCRIPTION:
Deadman 65 3.0
END DESCRIPTION:
XS GIS Cut Line= 3
      1640554.99      6857838.03      1640105.00      6858638.00
      1640105.00      6858737.95
#Sta/Elev= 30
  4081.7 1857.95  4095.4 1857.06  4111.3 1854.92  4213.9 1847.21  4235.6 1846.58
  4294.9 1842.42  4368.5 1838.61  4403.2 1835.18  4435.1 1833.23  4552.1 1829.43
  4689.8 1826.85  4727.1 1827.17  4786.3 1825.95  4845.6 1826.77  4926.6 1826.02
  4948.2 1825.20  4954.0 1823.89  4964.2 1824.70  4976.6 1822.28  4991.6 1821.44
  4996.7 1819.70  5016.7 1818.13  5017.1 1817.63  5022.4 1818.13  5029.5 1818.65
  5039.5 1821.31  5049.5 1824.46  5059.5 1828.67  5069.5 1831.19  5099.5 1836.16
#Mann=3,-1,0
  4081.7    0.05       0  5016.7    0.05       0  5022.4    0.05       0
Bank Sta=5016.7,5022.4
Exp/Cntr=0.3,0.1

Type RM Length L Ch R = 1,1766,281,281,281
BEGIN DESCRIPTION:
Deadman 65 2.0
END DESCRIPTION:
XS GIS Cut Line= 3
      1640455.02      6857637.98      1639705.00      6858438.00
      1639654.99      6858638.03
#Sta/Elev= 30
  3899.0 1867.29  3934.4 1864.47  4047.8 1858.61  4160.6 1848.26  4196.2 1845.58
  4302.3 1839.46  4337.7 1836.51  4358.9 1833.55  4401.4 1831.30  4578.2 1827.44
  4592.4 1826.44  4627.6 1826.48  4655.9 1825.25  4670.1 1825.59  4840.0 1823.15
  4868.4 1823.88  4896.7 1823.59  4960.2 1821.93  4988.5 1820.39  4992.2 1819.47
  5010.8 1818.33  5011.3 1817.83  5016.5 1818.33  5036.8 1819.88  5054.9 1822.48
  5101.3 1824.65  5119.3 1826.67  5142.5 1830.46  5160.5 1834.27  5201.8 1839.96
#Mann=3,-1,0
  3899.0    0.05       0  5010.8    0.03       0  5016.5    0.05       0
Bank Sta=5010.8,5016.5
Exp/Cntr=0.3,0.1

Type RM Length L Ch R = 1,1485,273,273,273
BEGIN DESCRIPTION:
Deadman 65 1.1
END DESCRIPTION:
XS GIS Cut Line= 3
      1639832.33      6857857.11      1639505.96      6858291.12
      1639388.27      6858644.19
#Sta/Elev= 30
  4457.7 1829.61  4557.0 1827.00  4592.4 1826.69  4627.8 1825.26  4771.5 1822.88
  4784.1 1823.30  4798.6 1822.63  4856.9 1822.37  4913.2 1819.90  4934.3 1820.29
  4963.1 1819.39  4977.7 1819.64  5008.0 1818.32  5018.8 1817.10  5019.2 1816.60
  5024.6 1817.10  5048.0 1818.20  5060.7 1821.36  5071.2 1822.23  5148.2 1821.37
  5211.4 1821.84  5243.0 1822.86  5282.1 1825.83  5306.3 1826.29  5313.7 1827.98
  5332.6 1829.72  5337.9 1829.23  5364.3 1830.39  5369.5 1829.80  5372.9 1830.39
#Mann=3,-1,0
  4457.7    0.05       0  5018.8    0.05       0  5024.6    0.05       0
Bank Sta=5018.8,5024.6
Exp/Cntr=0.3,0.1

Type RM Length L Ch R = 1,1212,342,342,342
BEGIN DESCRIPTION:
Deadman 65 1.2
END DESCRIPTION:
XS GIS Cut Line= 3
      1639703.90      6857690.40      1639339.29      6858089.73
      1639269.91      6858530.26
#Sta/Elev= 30
  4460.3 1833.43  4464.9 1832.49  4485.9 1831.18  4507.5 1828.16  4514.3 1828.03
  4528.5 1825.23  4571.0 1827.79  4606.2 1827.61  4656.1 1826.03  4662.9 1825.18
  4727.1 1824.22  4748.0 1823.11  4833.1 1822.39  4931.8 1820.09  4974.4 1819.86
  4988.5 1819.22  4996.0 1816.53  5000.5 1816.99  5006.5 1815.59  5007.0 1815.09
  5012.3 1815.59  5039.8 1817.49  5110.6 1819.55  5171.4 1819.40  5187.9 1820.33
  5222.0 1820.71  5313.0 1820.38  5385.6 1821.39  5443.1 1823.64  5447.0 1823.17
#Mann=3,-1,0
  4460.3    0.05       0  5006.5    0.05       0  5012.3    0.05       0
Bank Sta=5006.5,5012.3
Exp/Cntr=0.3,0.1

Type RM Length L Ch R = 1,870,629,629,629
BEGIN DESCRIPTION:
Deadman 65 1.3
END DESCRIPTION:
XS GIS Cut Line= 3
      1639488.62      6857617.47      1639058.04      6858200.85
      1639058.04      6858558.48
#Sta/Elev= 30
  4252.6 1824.76  4263.3 1825.36  4284.1 1824.45  4313.4 1824.27  4369.7 1822.77
  4384.4 1822.98  4505.5 1820.89  4576.4 1820.53  4605.7 1819.74  4620.3 1820.05
  4705.9 1818.19  4726.8 1818.03  4770.7 1818.83  4791.5 1818.31  4820.8 1819.09
  4870.9 1817.20  4935.7 1817.08  4941.9 1815.57  4949.3 1816.00  4956.5 1815.63
  4962.7 1814.03  4968.1 1813.82  4968.6 1813.32  4973.6 1813.32  4974.1 1813.82
  4976.0 1815.22  4994.8 1815.98  5014.8 1818.92  5024.8 1819.87  5335.3 1824.84
#Mann=3,-1,0
  4252.6    0.05       0  4968.1    0.05       0  4974.1    0.05       0
Bank Sta=4968.1,4974.1
Exp/Cntr=0.3,0.1

Type RM Length L Ch R = 1,241,0,0,0
BEGIN DESCRIPTION:
Deadman 65 1.0
END DESCRIPTION:
XS GIS Cut Line= 3
      1639556.18      6857393.26      1638908.96      6857734.39
      1639036.36      6858671.76
#Sta/Elev= 30
  4262.1 1837.28  4309.4 1834.85  4325.7 1832.31  4430.2 1823.78  4771.4 1817.93
  4881.5 1817.52  4903.5 1815.79  4909.2 1812.86  4919.1 1812.94  4925.6 1814.42
  4931.2 1810.72  4941.7 1811.71  4947.6 1815.18  4953.2 1812.13  4964.0 1815.63
  4969.6 1813.46  4975.6 1815.43  4986.0 1816.45  4991.6 1814.96  4997.6 1815.54
  5007.5 1812.46  5017.5 1811.93  5024.6 1809.60  5025.1 1809.10  5030.7 1809.60
  5068.0 1810.88  5088.2 1814.22  5146.8 1817.01  5491.9 1819.55  5939.7 1826.02
#Mann=3,-1,0
  4262.1    0.05       0  5024.6    0.05       0  5030.7    0.05       0
Bank Sta=5024.6,5030.7
Exp/Cntr=0.3,0.1

Chan Stop Cuts=-1