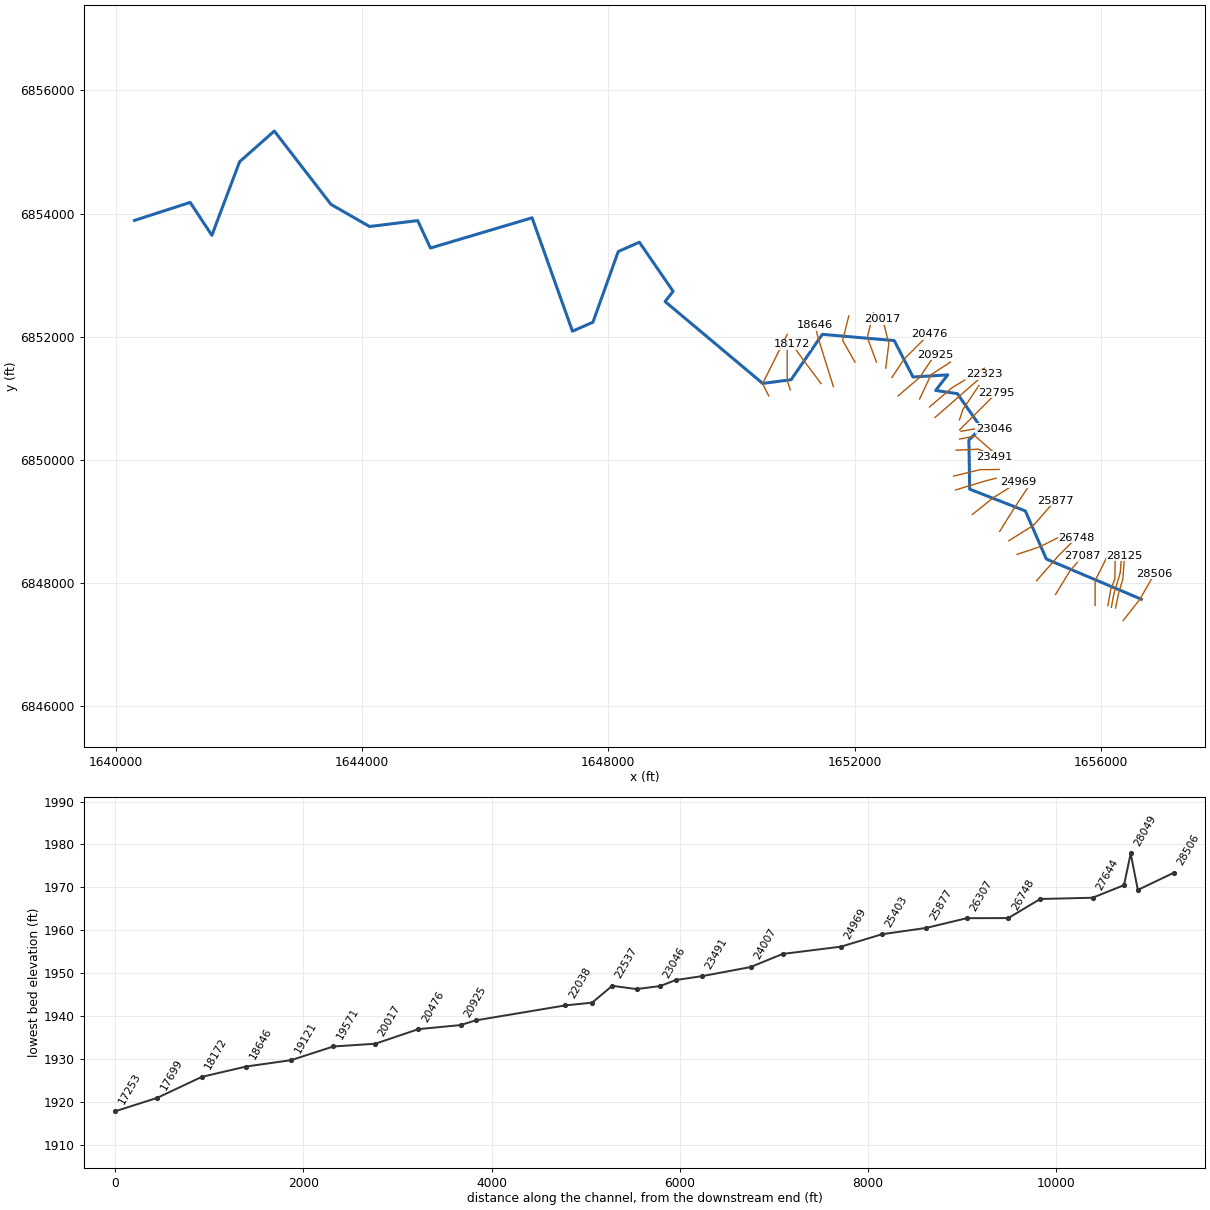
--- Deadman 66.prj (project) ---

Proj Title=Deadman 66 Base Level Engineering
Current Plan=p01
Default Exp/Contr=0.3,0.1
English Units
Geom File=g01
Flow File=f01
Plan File=p01
Y Axis Title=Elevation
X Axis Title(PF)=Main Channel Distance
X Axis Title(XS)=Station
BEGIN DESCRIPTION:
Deadman 66
END DESCRIPTION:
DSS Export Rating Curves= 0
DSS Export Rating Curve Sorted= 0
DSS Export Volume Flow Curves= 0
DXF OffsetX= 0
DXF OffsetY= 0
DXF ScaleX= 1
DXF ScaleY= 10

--- Deadman 66.p01 (plan) ---

Plan Title=Multiple Run
Short Identifier=Multiple
Geom File=g01
Flow File=f01
Subcritical Flow
K Sum by GR= 0
Std Step Tol= 0.01
Critical Tol= 0.01
Num of Std Step Trials= 20
Max Error Tol= 0.3
Flow Tol Ratio= 0.001
Split Flow NTrial= 30
Split Flow Tol= 0.02
Split Flow Ratio= 0.02
Log Output Level= 0
Friction Slope Method= 1
Unsteady Friction Slope Method= 2
Unsteady Bridges Friction Slope Method= 1
Parabolic Critical Depth
Global Vel Dist=  1 , 1 , 1
Global Log Level= 0
CheckData=True
Encroach Param= -1, 0, 0, 0
BEGIN DESCRIPTION:
Multiple Run
END DESCRIPTION:

--- Deadman 66.f01 (steady flow) ---

Flow Title=Multiple
Number of Profiles=7
Profile Names=10-year,25-year,50-year,1pct_min,100-year,1pct_plu,500-year
River Rch & RM= Deadman 66,Reach-1,28506
     193     259     313     188     375     748     544
River Rch & RM= Deadman 66,Reach-1,28125
     313     433     532     325     649    1294     977
River Rch & RM= Deadman 66,Reach-1,20017
     418     588     730     451     899    1794    1381
River Rch & RM= Deadman 66,Reach-1,14079
     537     767     962     599    1196    2386    1873
River Rch & RM= Deadman 66,Reach-1,5444
     602     865    1089     681    1358    2710    2143
Boundary for River Rch & Prof#=Deadman 66,Reach-1,1
Up Type=0
Dn Type=3
Dn Slope=0.009
Boundary for River Rch & Prof#=Deadman 66,Reach-1,2
Up Type=0
Dn Type=3
Dn Slope=0.009
Boundary for River Rch & Prof#=Deadman 66,Reach-1,3
Up Type=0
Dn Type=3
Dn Slope=0.009
Boundary for River Rch & Prof#=Deadman 66,Reach-1,4
Up Type=0
Dn Type=3
Dn Slope=0.009
Boundary for River Rch & Prof#=Deadman 66,Reach-1,5
Up Type=0
Dn Type=3
Dn Slope=0.009
Boundary for River Rch & Prof#=Deadman 66,Reach-1,6
Up Type=0
Dn Type=3
Dn Slope=0.009
Boundary for River Rch & Prof#=Deadman 66,Reach-1,7
Up Type=0
Dn Type=3
Dn Slope=0.009

--- Deadman 66.g01 (geometry) ---

Geom Title=Existing Conditions

River Reach=Deadman 66,Reach-1
Reach XY= 30
      1656655.00      6847738.00      1655113.48      6848390.63
      1654771.79      6849171.56      1653868.32      6849524.66
      1653855.66      6850322.17      1654054.83      6850521.96
      1653668.63      6851075.05      1653315.79      6851127.63
      1653511.57      6851380.31      1652948.55      6851345.74
      1652643.00      6851936.84      1651475.23      6852038.50
      1650968.22      6851301.62      1650506.58      6851241.67
      1648921.00      6852571.05      1649051.91      6852736.32
      1648503.50      6853534.54      1648160.58      6853382.42
      1647749.58      6852235.32      1647417.01      6852089.17
      1646761.21      6853930.20      1645111.02      6853439.61
      1644903.37      6853884.87      1644120.94      6853788.92
      1643495.21      6854148.43      1642575.34      6855338.78
      1642010.77      6854840.53      1641561.05      6853645.46
      1641208.62      6854180.52      1640305.00      6853888.00

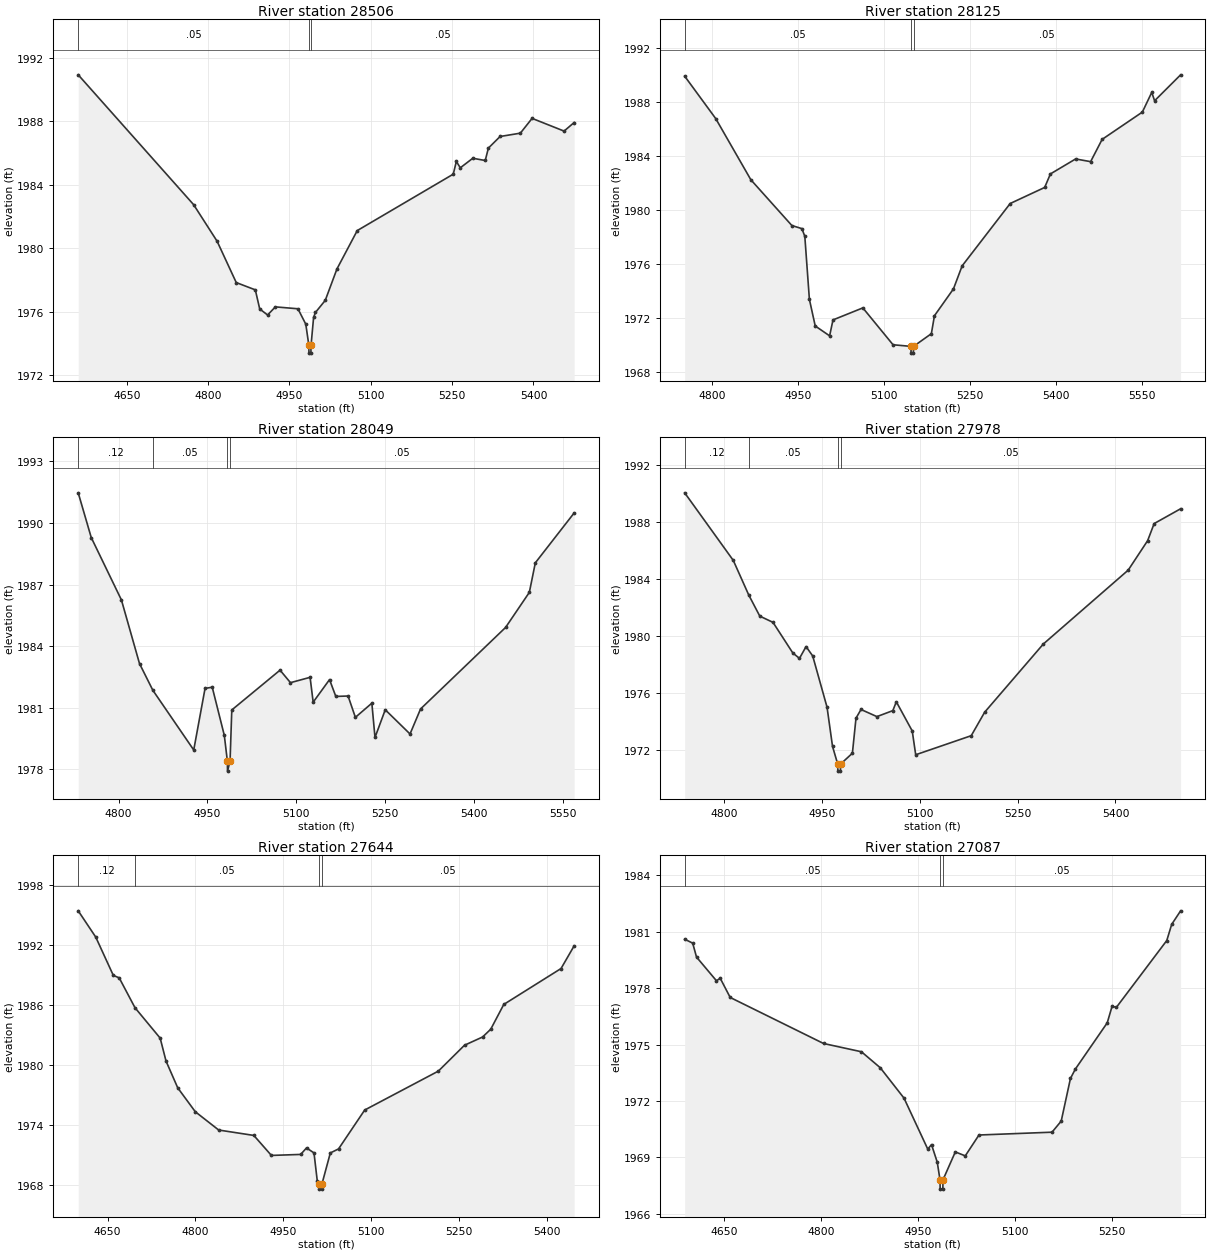
Type RM Length L Ch R = 1,28506,381,381,381
BEGIN DESCRIPTION:
Deadman 66 49.0
END DESCRIPTION:
XS GIS Cut Line= 3
      1656361.19      6847392.10      1656631.77      6847735.97
      1656868.55      6848150.33
#Sta/Elev= 30
  4560.3 1990.91  4773.2 1982.74  4816.5 1980.44  4851.8 1977.84  4887.0 1977.38
  4895.1 1976.18  4909.6 1975.80  4924.0 1976.31  4965.6 1976.19  4980.1 1975.22
  4985.7 1973.90  4985.9 1973.40  4989.5 1973.40  4989.8 1973.90  4994.5 1975.65
  4997.9 1975.96  5016.0 1976.72  5037.6 1978.70  5075.0 1981.11  5252.1 1984.66
  5257.8 1985.46  5265.1 1985.06  5288.1 1985.66  5311.1 1985.52  5316.9 1986.30
  5338.5 1987.03  5375.9 1987.24  5397.5 1988.17  5456.5 1987.37  5475.1 1987.91
#Mann=3,-1,0
  4560.3    0.05       0  4985.7    0.03       0  4989.8    0.05       0
Bank Sta=4985.7,4989.8
Exp/Cntr=0.3,0.1

Type RM Length L Ch R = 1,28125,76,76,76
BEGIN DESCRIPTION:
Mapping XS d47d46eb
END DESCRIPTION:
XS GIS Cut Line= 4
      1656237.17      6847595.01      1656287.91      6847834.62
      1656355.55      6848065.74      1656383.62      6848444.66
#Sta/Elev= 30
  4751.9 1989.93  4806.1 1986.79  4867.4 1982.26  4939.0 1978.87  4956.5 1978.64
  4961.6 1978.07  4969.6 1973.40  4979.8 1971.43  5004.9 1970.70  5010.8 1971.88
  5062.9 1972.77  5115.6 1970.04  5146.8 1969.92  5147.1 1969.42  5151.0 1969.42
  5151.4 1969.92  5182.5 1970.86  5187.9 1972.19  5221.1 1974.18  5236.2 1975.88
  5320.1 1980.50  5380.3 1981.69  5390.3 1982.69  5434.3 1983.80  5460.5 1983.60
  5480.6 1985.25  5550.8 1987.27  5567.2 1988.73  5572.2 1988.11  5617.6 1990.03
#Mann=3,-1,0
  4751.9    0.05       0  5146.8    0.05       0  5151.4    0.05       0
Bank Sta=5146.8,5151.4
Exp/Cntr=0.3,0.1

Type RM Length L Ch R = 1,28049,71,71,71
BEGIN DESCRIPTION:
Mapping XS 628d7618
END DESCRIPTION:
XS GIS Cut Line= 4
      1656169.53      6847606.34      1656208.99      6847820.53
      1656313.28      6848167.21      1656332.98      6848423.34
#Sta/Elev= 30
  4732.0 1991.47  4754.0 1989.29  4804.9 1986.25  4835.4 1983.15  4857.9 1981.85
  4926.9 1978.94  4946.0 1981.94  4958.1 1982.00  4978.5 1979.65  4983.6 1978.41
  4983.9 1977.91  4988.2 1978.41  4991.1 1980.89  5072.5 1982.83  5090.1 1982.22
  5123.2 1982.48  5128.4 1981.27  5156.0 1982.37  5166.6 1981.55  5187.3 1981.57
  5199.6 1980.53  5227.4 1981.22  5232.7 1979.55  5250.0 1980.90  5291.8 1979.72
  5309.6 1980.94  5453.0 1984.91  5493.1 1986.62  5503.2 1988.06  5568.7 1990.49
#Mann=4,-1,0
  4732.0    0.12       0  4857.9    0.05       0  4983.6    0.05       0
  4988.2    0.05       0
Bank Sta=4983.6,4988.2
Exp/Cntr=0.3,0.1

Type RM Length L Ch R = 1,27978,334,334,334
BEGIN DESCRIPTION:
Mapping XS 71d45a35
END DESCRIPTION:
XS GIS Cut Line= 4
      1656113.16      6847634.53      1656158.25      6847893.81
      1656225.90      6848065.74      1656231.54      6848378.56
#Sta/Elev= 30
  4739.1 1990.08  4813.7 1985.33  4837.3 1982.91  4854.3 1981.42  4874.6 1980.98
  4905.0 1978.83  4915.2 1978.45  4925.3 1979.28  4935.5 1978.62  4957.5 1975.02
  4965.9 1972.27  4973.8 1971.03  4974.1 1970.53  4978.0 1970.53  4978.4 1971.03
  4996.4 1971.79  5001.9 1974.25  5009.6 1974.86  5034.0 1974.36  5058.4 1974.78
  5063.8 1975.40  5088.2 1973.35  5093.5 1971.68  5178.7 1973.02  5199.3 1974.67
  5289.3 1979.46  5419.5 1984.65  5449.3 1986.72  5459.3 1987.92  5499.9 1988.96
#Mann=4,-1,0
  4739.1    0.12       0  4837.3    0.05       0  4973.8    0.05       0
  4978.4    0.05       0
Bank Sta=4973.8,4978.4
Exp/Cntr=0.3,0.1

Type RM Length L Ch R = 1,27644,557,557,557
BEGIN DESCRIPTION:
Deadman 66 48.0
END DESCRIPTION:
XS GIS Cut Line= 3
      1655905.00      6847638.01      1655905.00      6848038.00
      1656105.00      6848437.99
#Sta/Elev= 30
  4599.9 1995.43  4629.9 1992.80  4659.9 1988.97  4669.9 1988.73  4696.9 1985.74
  4739.9 1982.70  4749.9 1980.41  4769.9 1977.73  4799.9 1975.34  4839.9 1973.51
  4899.9 1972.97  4929.9 1970.97  4979.9 1971.07  4989.9 1971.72  5002.7 1971.22
  5008.3 1968.41  5011.6 1968.10  5011.9 1967.60  5015.9 1967.60  5016.2 1968.10
  5030.6 1971.22  5044.6 1971.62  5089.3 1975.51  5215.1 1979.40  5259.8 1981.99
  5290.6 1982.81  5304.6 1983.59  5326.9 1986.07  5424.7 1989.66  5447.1 1991.93
#Mann=4,-1,0
  4599.9    0.12       0  4696.9    0.05       0  5011.6    0.03       0
  5016.2    0.05       0
Bank Sta=5011.6,5016.2
Exp/Cntr=0.3,0.1

Type RM Length L Ch R = 1,27087,339,339,339
BEGIN DESCRIPTION:
Deadman 66 47.0
END DESCRIPTION:
XS GIS Cut Line= 3
      1655261.97      6847814.92      1655498.71      6848201.03
      1655705.01      6848438.01
#Sta/Elev= 30
  4588.5 1980.61  4600.9 1980.40  4606.8 1979.66  4637.6 1978.40  4643.5 1978.53
  4658.9 1977.51  4803.3 1975.06  4861.9 1974.62  4891.0 1973.77  4927.8 1972.15
  4964.5 1969.44  4970.3 1969.68  4979.2 1968.74  4983.4 1967.81  4983.7 1967.31
  4987.8 1967.31  4988.1 1967.81  5007.1 1969.29  5022.5 1969.08  5043.7 1970.19
  5156.7 1970.34  5170.9 1970.93  5185.2 1973.20  5192.8 1973.70  5242.1 1976.16
  5249.5 1977.03  5256.4 1976.99  5334.2 1980.54  5341.8 1981.40  5355.6 1982.12
#Mann=3,-1,0
  4588.5    0.05       0  4983.4    0.03       0  4988.1    0.05       0
Bank Sta=4983.4,4988.1
Exp/Cntr=0.3,0.1

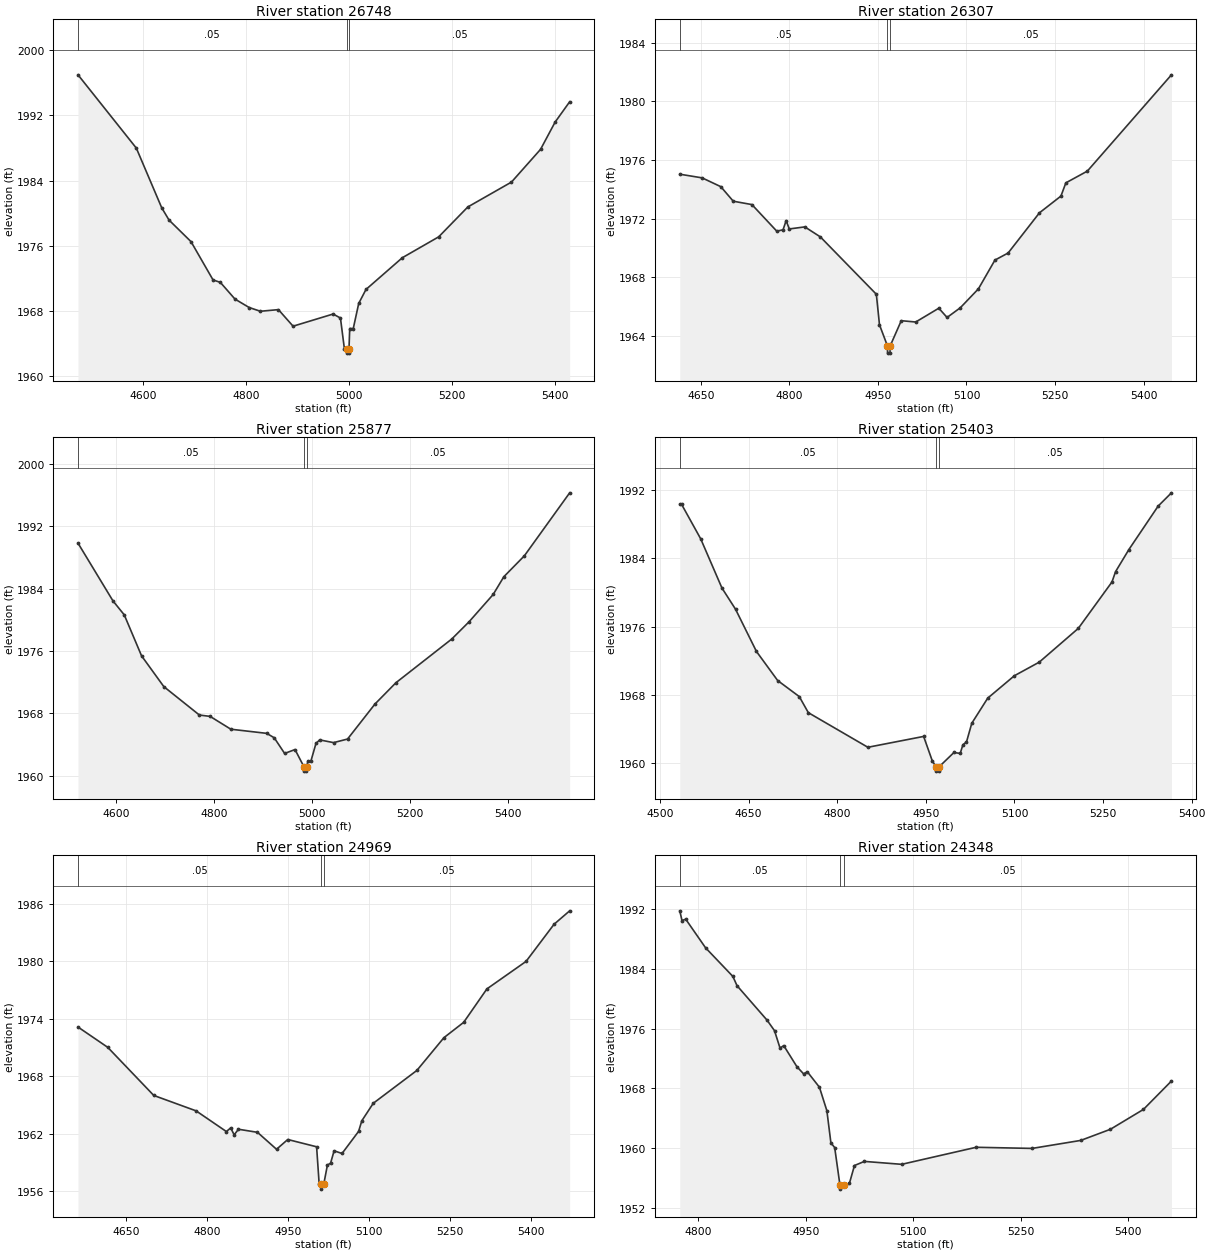
Type RM Length L Ch R = 1,26748,441,441,441
BEGIN DESCRIPTION:
Deadman 66 46.0
END DESCRIPTION:
XS GIS Cut Line= 3
      1654954.98      6848037.98      1655305.00      6848438.00
      1655605.00      6848738.00
#Sta/Elev= 30
  4472.8 1996.96  4586.2 1987.98  4635.6 1980.66  4649.8 1979.16  4692.5 1976.52
  4735.3 1971.83  4749.5 1971.53  4778.0 1969.48  4805.5 1968.45  4827.3 1967.99
  4862.4 1968.19  4890.9 1966.16  4968.7 1967.65  4983.0 1967.16  4990.6 1963.42
  4994.8 1963.36  4995.2 1962.86  4999.3 1962.86  4999.6 1963.36  5001.0 1965.87
  5007.9 1965.87  5018.5 1968.95  5032.6 1970.66  5103.3 1974.55  5174.0 1977.11
  5230.6 1980.77  5315.5 1983.82  5372.0 1987.83  5400.3 1991.17  5428.6 1993.66
#Mann=3,-1,0
  4472.8    0.05       0  4994.8    0.03       0  4999.6    0.05       0
Bank Sta=4994.8,4999.6
Exp/Cntr=0.3,0.1

Type RM Length L Ch R = 1,26307,430,430,430
BEGIN DESCRIPTION:
Deadman 66 45.0
END DESCRIPTION:
XS GIS Cut Line= 3
      1654639.09      6848465.99      1655005.00      6848588.00
      1655404.97      6848787.99
#Sta/Elev= 30
  4614.4 1975.03  4652.3 1974.78  4683.9 1974.18  4705.0 1973.19  4736.6 1972.96
  4778.7 1971.15  4789.3 1971.24  4794.6 1971.87  4799.9 1971.30  4826.2 1971.44
  4852.5 1970.76  4947.4 1966.85  4952.7 1964.77  4966.1 1963.34  4966.4 1962.84
  4970.5 1962.84  4970.9 1963.34  4989.6 1965.05  5014.1 1964.96  5053.2 1965.90
  5067.2 1965.27  5089.6 1965.93  5120.3 1967.22  5148.3 1969.18  5170.6 1969.66
  5223.7 1972.40  5260.1 1973.54  5268.4 1974.44  5304.8 1975.24  5447.3 1981.80
#Mann=3,-1,0
  4614.4    0.05       0  4966.1    0.05       0  4970.9    0.05       0
Bank Sta=4966.1,4970.9
Exp/Cntr=0.3,0.1

Type RM Length L Ch R = 1,25877,474,474,474
BEGIN DESCRIPTION:
Deadman 66 44.0
END DESCRIPTION:
XS GIS Cut Line= 3
      1654504.99      6848687.99      1654905.00      6848938.00
      1655254.99      6849337.98
#Sta/Elev= 30
  4522.1 1989.85  4593.5 1982.43  4616.5 1980.64  4651.8 1975.38  4697.2 1971.43
  4769.8 1967.78  4791.6 1967.61  4834.0 1965.96  4907.1 1965.43  4922.5 1964.86
  4943.7 1962.85  4964.9 1963.35  4983.6 1961.08  4984.0 1960.58  4988.3 1960.58
  4988.6 1961.08  4990.9 1961.82  4997.1 1961.82  5007.6 1964.13  5015.2 1964.59
  5043.6 1964.24  5072.1 1964.70  5128.1 1969.20  5170.8 1971.93  5284.7 1977.54
  5319.8 1979.74  5369.2 1983.26  5391.0 1985.54  5432.8 1988.22  5525.3 1996.31
#Mann=3,-1,0
  4522.1    0.05       0  4983.6    0.05       0  4988.6    0.05       0
Bank Sta=4983.6,4988.6
Exp/Cntr=0.3,0.1

Type RM Length L Ch R = 1,25403,434,434,434
BEGIN DESCRIPTION:
Deadman 66 43.0
END DESCRIPTION:
XS GIS Cut Line= 3
      1654354.98      6848837.96      1654605.00      6849238.00
      1654805.00      6849538.00
#Sta/Elev= 30
  4533.5 1990.31  4536.5 1990.31  4568.9 1986.27  4604.9 1980.51  4627.9 1978.03
  4663.3 1973.09  4699.2 1969.69  4735.8 1967.81  4751.1 1965.93  4851.9 1961.88
  4946.3 1963.15  4961.0 1960.28  4967.3 1959.59  4967.7 1959.09  4972.0 1959.09
  4972.4 1959.59  4997.6 1961.27  5008.2 1961.16  5012.8 1962.18  5018.8 1962.49
  5027.8 1964.69  5054.8 1967.63  5099.9 1970.25  5142.0 1971.84  5208.1 1975.79
  5265.1 1981.22  5271.2 1982.43  5293.7 1985.01  5343.3 1990.10  5365.8 1991.65
#Mann=3,-1,0
  4533.5    0.05       0  4967.3    0.05       0  4972.4    0.05       0
Bank Sta=4967.3,4972.4
Exp/Cntr=0.3,0.1

Type RM Length L Ch R = 1,24969,621,621,621
BEGIN DESCRIPTION:
Deadman 66 42.0
END DESCRIPTION:
XS GIS Cut Line= 3
      1653911.89      6849114.27      1654255.00      6849388.00
      1654654.99      6849637.99
#Sta/Elev= 30
  4561.3 1973.13  4616.4 1971.01  4701.6 1965.99  4780.0 1964.38  4836.1 1962.22
  4844.1 1962.60  4850.5 1961.88  4858.5 1962.46  4893.7 1962.14  4929.0 1960.37
  4949.8 1961.39  5003.2 1960.63  5007.9 1956.79  5011.2 1956.71  5011.6 1956.21
  5016.4 1956.71  5023.2 1958.72  5029.1 1958.92  5035.6 1960.21  5050.3 1959.93
  5081.0 1962.24  5086.9 1963.34  5108.1 1965.17  5188.9 1968.60  5239.0 1972.02
  5275.6 1973.62  5318.6 1977.11  5391.1 1979.98  5443.0 1983.86  5471.9 1985.26
#Mann=3,-1,0
  4561.3    0.05       0  5011.2    0.05       0  5016.4    0.05       0
Bank Sta=5011.2,5016.4
Exp/Cntr=0.3,0.1

Type RM Length L Ch R = 1,24348,341,341,341
BEGIN DESCRIPTION:
Mapping XS b1400eb1
END DESCRIPTION:
XS GIS Cut Line= 3
      1653638.50      6849511.68      1654075.34      6849644.14
      1654297.35      6849703.15
#Sta/Elev= 30
  4774.0 1991.76  4777.1 1990.46  4782.3 1990.64  4810.0 1986.81  4848.1 1982.98
  4853.9 1981.74  4895.7 1977.14  4906.2 1975.72  4913.9 1973.39  4919.1 1973.72
  4937.5 1970.89  4946.8 1969.94  4952.0 1970.22  4968.9 1968.15  4979.3 1965.00
  4984.9 1960.71  4990.2 1960.07  4997.6 1955.01  4998.0 1954.51  5002.8 1955.01
  5010.7 1955.27  5017.8 1957.67  5031.6 1958.22  5083.7 1957.83  5187.6 1960.11
  5265.7 1959.96  5333.6 1961.03  5375.0 1962.52  5421.1 1965.18  5460.2 1968.98
#Mann=3,-1,0
  4774.0    0.05       0  4997.6    0.05       0  5002.8    0.05       0
Bank Sta=4997.6,5002.8
Exp/Cntr=0.3,0.1

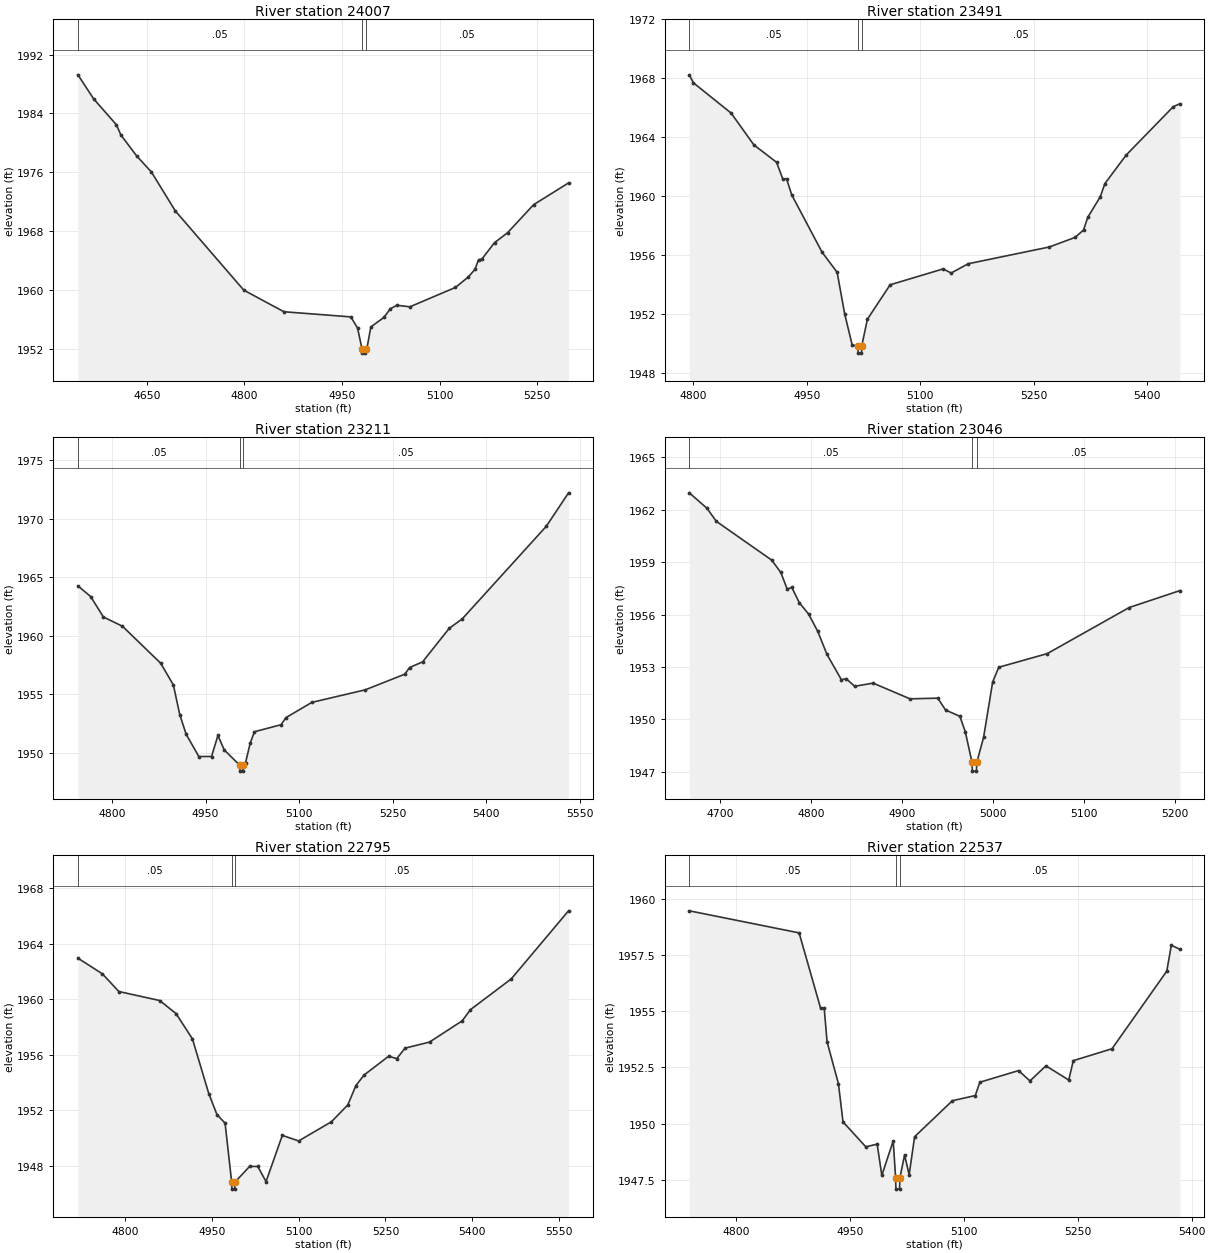
Type RM Length L Ch R = 1,24007,516,516,516
BEGIN DESCRIPTION:
Deadman 66 41.0
END DESCRIPTION:
XS GIS Cut Line= 3
      1653607.45      6849737.15      1654038.70      6849841.43
      1654348.71      6849844.25
#Sta/Elev= 30
  4544.2 1989.24  4568.3 1985.98  4603.4 1982.45  4610.1 1981.08  4634.3 1978.24
  4657.1 1976.04  4693.8 1970.76  4798.9 1960.01  4860.6 1957.07  4963.5 1956.37
  4973.8 1954.85  4980.8 1951.95  4981.2 1951.45  4985.6 1951.45  4986.0 1951.95
  4987.9 1951.95  4994.2 1955.01  5014.2 1956.29  5024.2 1957.48  5034.2 1957.95
  5054.2 1957.74  5124.2 1960.37  5144.2 1961.81  5154.2 1962.83  5159.6 1964.13
  5164.6 1964.20  5184.2 1966.45  5204.2 1967.79  5244.2 1971.60  5297.9 1974.56
#Mann=3,-1,0
  4544.2    0.05       0  4980.8    0.05       0  4986.0    0.05       0
Bank Sta=4980.8,4986
Exp/Cntr=0.3,0.1

Type RM Length L Ch R = 1,23491,280,280,280
BEGIN DESCRIPTION:
Mapping XS 01bd76f8
END DESCRIPTION:
XS GIS Cut Line= 3
      1653649.71      6850157.11      1654013.33      6850174.02
      1654269.81      6850050.01
#Sta/Elev= 30
  4794.5 1968.24  4799.8 1967.70  4849.8 1965.64  4879.9 1963.48  4909.9 1962.30
  4918.1 1961.17  4923.1 1961.18  4929.9 1960.09  4970.0 1956.20  4990.0 1954.83
  5000.0 1952.00  5010.0 1949.87  5017.4 1949.84  5017.8 1949.34  5022.2 1949.34
  5022.6 1949.84  5030.0 1951.64  5060.1 1953.98  5130.2 1955.06  5140.8 1954.78
  5163.4 1955.41  5270.8 1956.55  5304.8 1957.20  5315.9 1957.70  5321.6 1958.57
  5338.1 1959.96  5344.1 1960.85  5372.3 1962.79  5434.5 1966.07  5443.4 1966.28
#Mann=3,-1,0
  4794.5    0.05       0  5017.4    0.05       0  5022.6    0.05       0
Bank Sta=5017.4,5022.6
Exp/Cntr=0.3,0.1

Type RM Length L Ch R = 1,23211,165,165,165
BEGIN DESCRIPTION:
Deadman 66 40.0
END DESCRIPTION:
XS GIS Cut Line= 3
      1653704.98      6850338.00      1653955.00      6850388.00
      1654355.02      6850037.99
#Sta/Elev= 30
  4745.4 1964.27  4765.8 1963.36  4786.2 1961.61  4816.8 1960.82  4878.0 1957.66
  4898.4 1955.80  4908.6 1953.27  4918.8 1951.59  4939.2 1949.68  4959.6 1949.68
  4969.8 1951.48  4980.0 1950.24  5004.9 1948.93  5005.3 1948.43  5009.7 1948.43
  5010.1 1948.93  5014.1 1949.15  5021.7 1950.85  5028.4 1951.80  5071.1 1952.40
  5078.7 1953.00  5120.4 1954.31  5205.9 1955.38  5269.4 1956.72  5277.0 1957.29
  5297.9 1957.77  5340.6 1960.64  5361.5 1961.45  5496.3 1969.37  5531.9 1972.23
#Mann=3,-1,0
  4745.4    0.05       0  5004.9    0.05       0  5010.1    0.05       0
Bank Sta=5004.9,5010.1
Exp/Cntr=0.3,0.1

Type RM Length L Ch R = 1,23046,251,251,251
BEGIN DESCRIPTION:
Mapping XS 27fd3c76
END DESCRIPTION:
XS GIS Cut Line= 3
      1653725.83      6850464.33      1654018.97      6850515.07
      1654260.71      6850503.83
#Sta/Elev= 30
  4666.4 1962.97  4685.9 1962.08  4696.0 1961.34  4756.9 1959.12  4767.0 1958.41
  4774.0 1957.46  4779.1 1957.55  4787.3 1956.68  4797.5 1956.03  4807.6 1955.04
  4817.8 1953.71  4833.7 1952.26  4838.8 1952.33  4848.2 1951.89  4868.5 1952.07
  4909.1 1951.17  4939.6 1951.21  4948.2 1950.53  4963.9 1950.17  4969.9 1949.28
  4977.3 1947.53  4977.7 1947.03  4982.1 1947.03  4982.5 1947.53  4990.0 1948.96
  5000.0 1952.14  5006.7 1952.98  5060.0 1953.76  5150.1 1956.40  5205.9 1957.37
#Mann=3,-1,0
  4666.4    0.05       0  4977.3    0.05       0  4982.5    0.05       0
Bank Sta=4977.3,4982.5
Exp/Cntr=0.3,0.1

Type RM Length L Ch R = 1,22795,258,258,258
BEGIN DESCRIPTION:
Deadman 66 39.0
END DESCRIPTION:
XS GIS Cut Line= 3
      1653705.01      6850488.01      1653905.00      6850688.00
      1654304.99      6851087.99
#Sta/Elev= 30
  4718.2 1962.96  4760.6 1961.83  4788.9 1960.56  4859.6 1959.91  4887.9 1958.97
  4916.2 1957.15  4944.5 1953.21  4958.6 1951.70  4972.7 1951.08  4984.1 1946.83
  4984.5 1946.33  4989.2 1946.33  4989.7 1946.83  5015.2 1947.97  5029.3 1947.96
  5043.5 1946.87  5071.7 1950.20  5100.0 1949.80  5156.6 1951.18  5184.9 1952.39
  5199.0 1953.79  5213.2 1954.55  5255.6 1955.90  5269.7 1955.73  5283.9 1956.48
  5326.3 1956.92  5382.9 1958.45  5397.0 1959.25  5467.7 1961.47  5566.7 1966.37
#Mann=3,-1,0
  4718.2    0.05       0  4984.1    0.05       0  4989.7    0.05       0
Bank Sta=4984.1,4989.7
Exp/Cntr=0.3,0.1

Type RM Length L Ch R = 1,22537,214,214,214
BEGIN DESCRIPTION:
Mapping XS 0fd8803e
END DESCRIPTION:
XS GIS Cut Line= 3
      1653703.28      6850650.33      1653756.84      6850816.66
      1654018.96      6851208.42
#Sta/Elev= 30
  4738.5 1959.46  4883.1 1958.48  4911.3 1955.14  4916.1 1955.14  4919.9 1953.64
  4934.9 1951.77  4940.9 1950.08  4970.9 1948.97  4985.9 1949.09  4992.0 1947.70
  5007.0 1949.23  5010.2 1947.59  5010.6 1947.09  5015.3 1947.09  5015.8 1947.59
  5022.0 1948.61  5028.0 1947.73  5035.2 1949.42  5085.0 1951.02  5115.1 1951.25
  5121.1 1951.84  5172.1 1952.36  5187.1 1951.90  5208.1 1952.57  5238.2 1951.94
  5244.2 1952.80  5295.2 1953.33  5367.3 1956.78  5373.3 1957.93  5384.6 1957.75
#Mann=3,-1,0
  4738.5    0.05       0  5010.2    0.05       0  5015.8    0.05       0
Bank Sta=5010.2,5015.8
Exp/Cntr=0.3,0.1

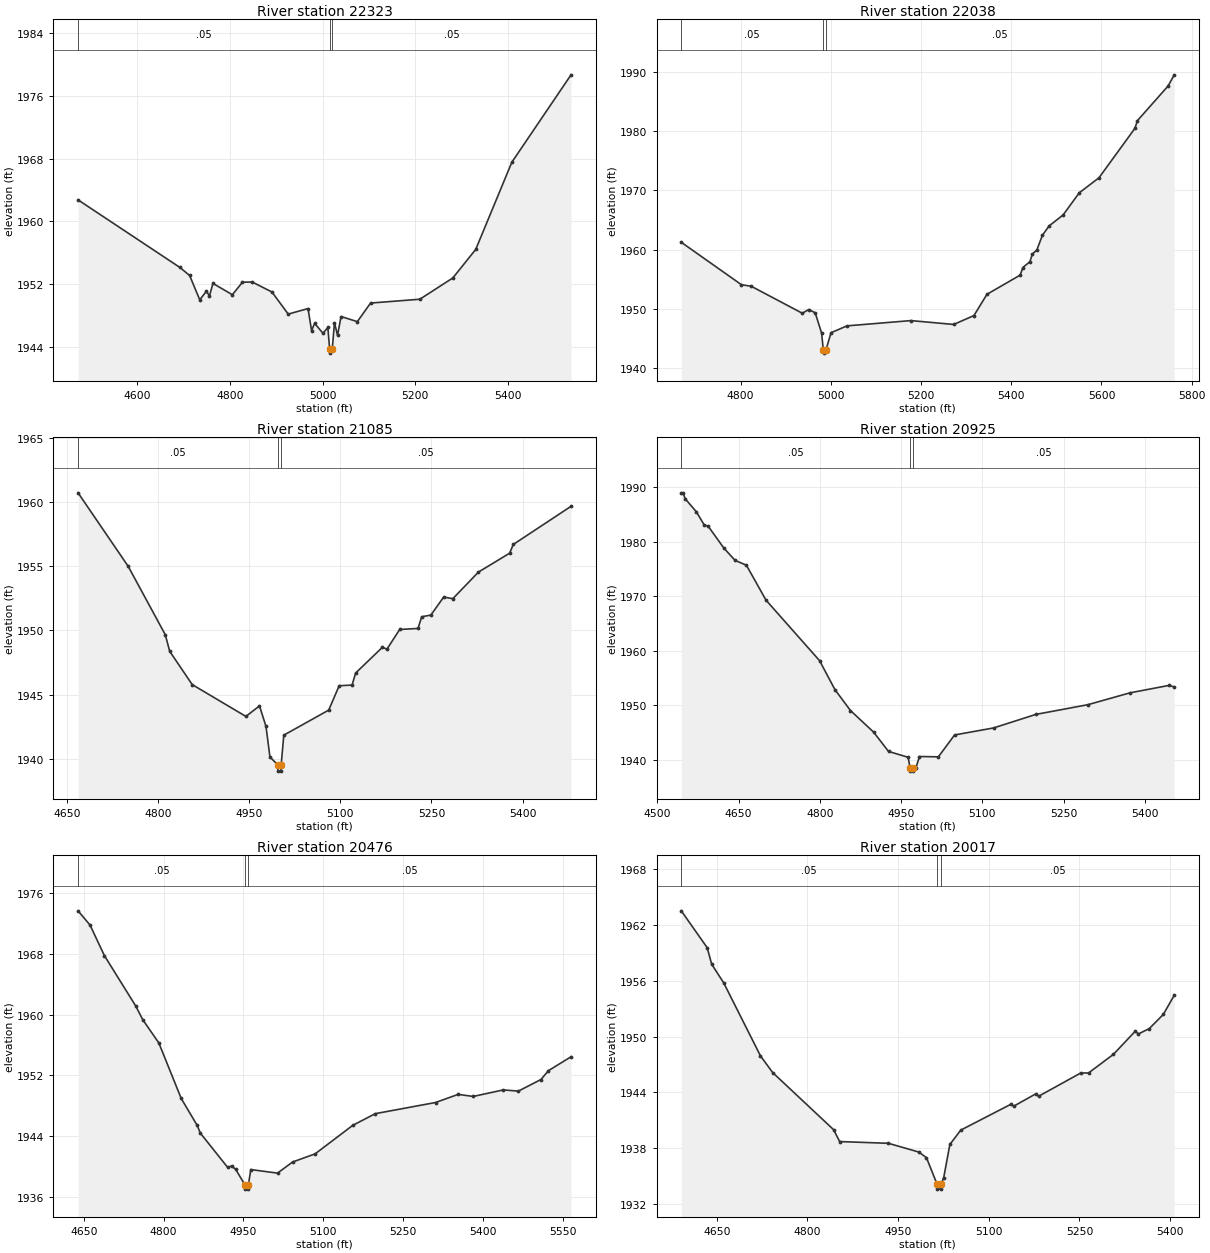
Type RM Length L Ch R = 1,22323,285,285,285
BEGIN DESCRIPTION:
Deadman 66 38.0
END DESCRIPTION:
XS GIS Cut Line= 3
      1653305.01      6850688.01      1653705.00      6851038.00
      1654105.00      6851388.00
#Sta/Elev= 30
  4472.8 1962.73  4692.5 1954.10  4713.4 1953.08  4735.2 1949.97  4749.5 1951.07
  4756.1 1950.47  4763.7 1952.07  4805.5 1950.62  4827.3 1952.22  4848.2 1952.25
  4890.9 1950.97  4926.0 1948.15  4968.7 1948.86  4976.3 1946.03  4982.9 1946.97
  5001.0 1945.70  5011.4 1946.45  5015.3 1943.67  5015.7 1943.17  5020.9 1943.67
  5025.7 1947.05  5032.3 1945.44  5039.9 1947.84  5075.0 1947.19  5103.5 1949.56
  5209.8 1950.05  5281.0 1952.77  5330.3 1956.41  5408.1 1967.53  5535.8 1978.69
#Mann=3,-1,0
  4472.8    0.05       0  5015.3    0.05       0  5020.9    0.05       0
Bank Sta=5015.3,5020.9
Exp/Cntr=0.3,0.1

Type RM Length L Ch R = 1,22038,953,953,953
BEGIN DESCRIPTION:
Deadman 66 37.0
END DESCRIPTION:
XS GIS Cut Line= 3
      1653215.69      6850858.94      1653582.09      6851171.80
      1654105.02      6851488.01
#Sta/Elev= 30
  4668.5 1961.24  4801.8 1954.08  4823.8 1953.81  4936.9 1949.26  4951.1 1949.89
  4965.4 1949.34  4979.7 1945.89  4983.4 1943.03  4983.9 1942.53  4989.1 1943.03
  5000.5 1945.97  5035.8 1947.13  5177.4 1948.02  5272.5 1947.37  5317.3 1948.87
  5346.2 1952.46  5419.9 1955.70  5425.8 1956.98  5441.3 1957.96  5447.1 1959.27
  5456.8 1959.94  5469.2 1962.43  5484.0 1964.00  5515.0 1965.85  5551.0 1969.60
  5594.5 1972.12  5674.1 1980.46  5679.9 1981.78  5747.8 1987.62  5761.4 1989.50
#Mann=3,-1,0
  4668.5    0.05       0  4983.4    0.05       0  4989.1    0.05       0
Bank Sta=4983.4,4989.1
Exp/Cntr=0.3,0.1

Type RM Length L Ch R = 1,21085,160,160,160
BEGIN DESCRIPTION:
Deadman 66 36.0
END DESCRIPTION:
XS GIS Cut Line= 3
      1653055.02      6850988.04      1653241.05      6851383.19
      1653555.00      6851588.00
#Sta/Elev= 30
  4668.2 1960.71  4750.7 1954.99  4811.8 1949.66  4819.1 1948.37  4856.1 1945.78
  4944.5 1943.30  4966.9 1944.12  4977.6 1942.52  4984.1 1940.14  4996.8 1939.54
  4997.3 1939.04  5002.1 1939.04  5002.6 1939.54  5006.9 1941.84  5080.8 1943.79
  5098.1 1945.69  5119.3 1945.74  5125.2 1946.68  5169.4 1948.69  5176.6 1948.53
  5197.7 1950.07  5227.9 1950.15  5233.9 1951.06  5249.0 1951.19  5270.1 1952.59
  5285.2 1952.47  5327.4 1954.54  5378.7 1956.01  5384.7 1956.69  5479.8 1959.66
#Mann=3,-1,0
  4668.2    0.05       0  4996.8    0.03       0  5002.6    0.05       0
Bank Sta=4996.8,5002.6
Exp/Cntr=0.3,0.1

Type RM Length L Ch R = 1,20925,449,449,449
BEGIN DESCRIPTION:
Deadman 66 35.0
END DESCRIPTION:
XS GIS Cut Line= 3
      1652705.00      6851038.00      1653055.00      6851338.00
      1653305.88      6851710.15
#Sta/Elev= 30
  4544.3 1988.98  4547.6 1988.98  4551.4 1987.91  4572.3 1985.48  4586.6 1983.09
  4594.2 1982.83  4622.8 1978.86  4643.6 1976.59  4664.5 1975.71  4700.7 1969.30
  4799.5 1958.21  4828.0 1952.88  4856.6 1949.06  4899.4 1945.09  4926.8 1941.56
  4963.0 1940.49  4966.7 1938.45  4967.2 1937.95  4972.1 1937.95  4972.5 1938.45
  4977.3 1938.52  4983.9 1940.63  5018.8 1940.57  5048.7 1944.58  5120.7 1945.87
  5198.7 1948.35  5294.6 1950.13  5372.6 1952.31  5444.5 1953.67  5454.1 1953.39
#Mann=3,-1,0
  4544.3    0.05       0  4966.7    0.03       0  4972.5    0.05       0
Bank Sta=4966.7,4972.5
Exp/Cntr=0.3,0.1

Type RM Length L Ch R = 1,20476,459,459,459
BEGIN DESCRIPTION:
Deadman 66 34.0
END DESCRIPTION:
XS GIS Cut Line= 3
      1652605.02      6851338.03      1652805.00      6851638.00
      1653205.00      6852038.00
#Sta/Elev= 30
  4639.2 1973.69  4661.7 1971.81  4688.7 1967.78  4747.3 1961.17  4760.9 1959.32
  4790.9 1956.28  4833.0 1948.95  4863.0 1945.40  4869.0 1944.38  4920.1 1939.88
  4927.6 1940.04  4935.1 1939.63  4953.3 1937.50  4953.7 1937.00  4958.6 1937.00
  4959.1 1937.50  4963.7 1939.58  5013.9 1939.11  5042.1 1940.57  5084.6 1941.65
  5155.3 1945.41  5197.7 1946.95  5310.8 1948.42  5353.3 1949.49  5381.6 1949.22
  5438.1 1950.08  5466.4 1949.92  5508.8 1951.45  5523.0 1952.62  5565.4 1954.45
#Mann=3,-1,0
  4639.2    0.05       0  4953.3    0.05       0  4959.1    0.05       0
Bank Sta=4953.3,4959.1
Exp/Cntr=0.3,0.1

Type RM Length L Ch R = 1,20017,446,446,446
BEGIN DESCRIPTION:
Deadman 66 33.0
END DESCRIPTION:
XS GIS Cut Line= 3
      1652505.01      6851488.04      1652555.00      6851888.00
      1652455.00      6852288.02
#Sta/Elev= 30
  4591.4 1963.55  4634.2 1959.59  4641.7 1957.81  4661.9 1955.76  4722.4 1947.94
  4742.5 1946.15  4843.3 1940.00  4853.4 1938.72  4934.0 1938.53  4984.4 1937.59
  4997.0 1936.98  5014.7 1934.10  5015.2 1933.60  5020.2 1933.60  5020.7 1934.10
  5025.4 1934.81  5035.7 1938.41  5053.7 1939.95  5136.2 1942.72  5141.4 1942.53
  5177.4 1943.84  5182.6 1943.60  5252.2 1946.10  5265.0 1946.10  5306.3 1948.11
  5342.4 1950.60  5347.5 1950.30  5365.6 1950.88  5388.7 1952.40  5406.8 1954.46
#Mann=3,-1,0
  4591.4    0.05       0  5014.7    0.05       0  5020.7    0.05       0
Bank Sta=5014.7,5020.7
Exp/Cntr=0.3,0.1

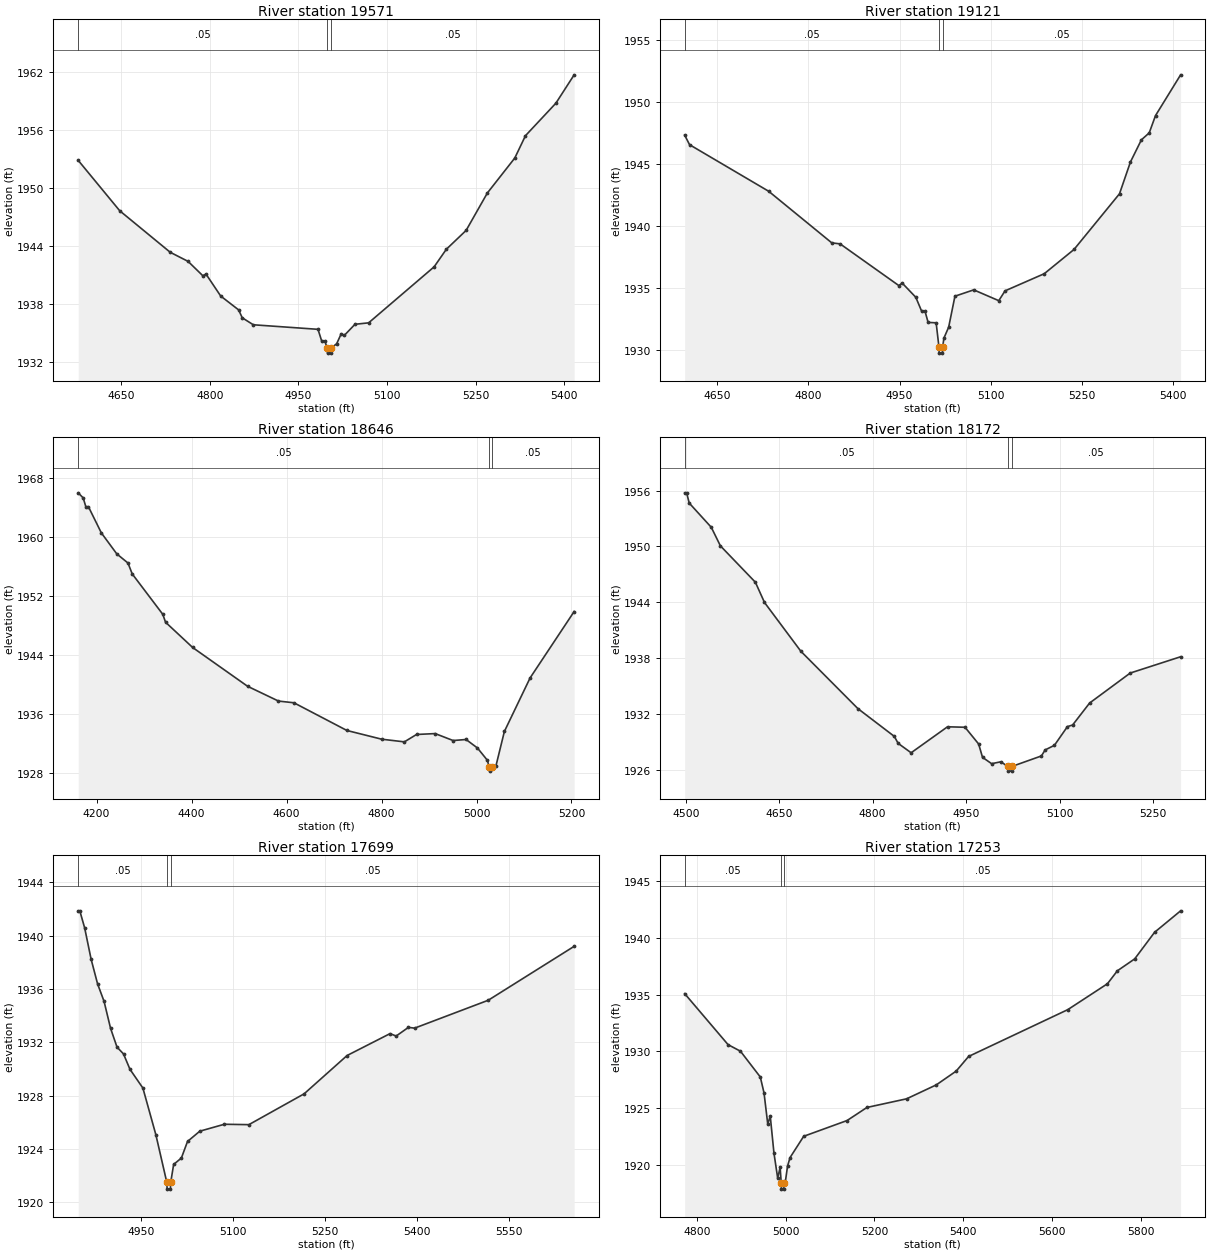
Type RM Length L Ch R = 1,19571,450,450,450
BEGIN DESCRIPTION:
Deadman 66 32.0
END DESCRIPTION:
XS GIS Cut Line= 3
      1652355.01      6851587.98      1652205.00      6851988.00
      1652304.99      6852387.97
#Sta/Elev= 30
  4577.2 1952.88  4647.5 1947.67  4733.0 1943.38  4763.2 1942.44  4788.1 1940.96
  4793.5 1941.13  4818.4 1938.86  4848.7 1937.43  4854.9 1936.61  4873.6 1935.89
  4983.1 1935.42  4989.3 1934.22  4994.6 1934.23  4998.7 1933.46  4999.2 1932.96
  5004.3 1932.96  5004.8 1933.46  5014.7 1933.93  5022.5 1934.97  5027.6 1934.79
  5045.7 1935.94  5068.8 1936.09  5179.7 1941.88  5200.3 1943.69  5233.8 1945.64
  5269.8 1949.51  5316.2 1953.12  5334.3 1955.43  5385.8 1958.79  5416.7 1961.72
#Mann=3,-1,0
  4577.2    0.05       0  4998.7    0.05       0  5004.8    0.05       0
Bank Sta=4998.7,5004.8
Exp/Cntr=0.3,0.1

Type RM Length L Ch R = 1,19121,475,475,475
BEGIN DESCRIPTION:
Deadman 66 31.0
END DESCRIPTION:
XS GIS Cut Line= 3
      1652005.02      6851587.97      1651805.00      6851938.00
      1651905.01      6852338.04
#Sta/Elev= 30
  4596.6 1947.31  4604.6 1946.54  4734.8 1942.79  4838.5 1938.64  4852.2 1938.56
  4948.6 1935.21  4954.4 1935.40  4976.7 1934.26  4986.1 1933.16  4991.8 1933.14
  4996.9 1932.24  5010.1 1932.21  5014.7 1930.27  5015.2 1929.77  5020.3 1929.77
  5020.8 1930.27  5022.9 1930.98  5030.7 1931.86  5041.0 1934.35  5071.9 1934.86
  5113.1 1933.99  5123.4 1934.78  5187.9 1936.16  5236.8 1938.11  5311.6 1942.59
  5329.6 1945.15  5347.6 1946.93  5360.5 1947.49  5370.8 1948.88  5412.1 1952.16
#Mann=3,-1,0
  4596.6    0.05       0  5014.7    0.05       0  5020.8    0.05       0
Bank Sta=5014.7,5020.8
Exp/Cntr=0.3,0.1

Type RM Length L Ch R = 1,18646,474,474,474
BEGIN DESCRIPTION:
Deadman 66 30.0
END DESCRIPTION:
XS GIS Cut Line= 3
      1651655.00      6851188.00      1651405.00      6851988.00
      1651355.00      6852187.99
#Sta/Elev= 30
  4161.3 1965.96  4171.8 1965.27  4177.5 1964.05  4182.8 1964.08  4210.0 1960.54
  4242.5 1957.70  4266.1 1956.46  4275.0 1954.99  4339.4 1949.52  4345.2 1948.45
  4402.3 1945.03  4518.0 1939.78  4583.0 1937.78  4615.5 1937.55  4727.1 1933.80
  4800.4 1932.62  4848.1 1932.26  4873.7 1933.26  4913.0 1933.38  4950.7 1932.44
  4978.0 1932.58  5002.0 1931.43  5022.6 1929.79  5027.3 1928.80  5027.8 1928.30
  5033.4 1928.80  5040.7 1928.95  5058.7 1933.67  5112.8 1940.91  5205.6 1949.90
#Mann=3,-1,0
  4161.3    0.05       0  5027.3    0.05       0  5033.4    0.05       0
Bank Sta=5027.3,5033.4
Exp/Cntr=0.3,0.1

Type RM Length L Ch R = 1,18172,473,473,473
BEGIN DESCRIPTION:
Deadman 66 29.0
END DESCRIPTION:
XS GIS Cut Line= 3
      1651455.00      6851238.00      1651155.00      6851638.00
      1650983.36      6851879.28
#Sta/Elev= 30
  4498.3 1955.76  4501.4 1955.76  4505.6 1954.66  4541.0 1952.06  4555.6 1950.07
  4611.8 1946.16  4626.4 1943.99  4684.8 1938.75  4776.4 1932.59  4834.8 1929.61
  4841.0 1928.86  4861.8 1927.85  4920.2 1930.64  4948.3 1930.59  4970.2 1928.79
  4976.4 1927.36  4991.0 1926.68  5005.7 1926.88  5017.3 1926.38  5017.8 1925.88
  5023.0 1925.88  5023.5 1926.38  5070.9 1927.51  5077.0 1928.16  5091.8 1928.65
  5112.7 1930.66  5121.0 1930.83  5148.3 1933.19  5213.5 1936.41  5294.4 1938.16
#Mann=3,-1,0
  4498.3    0.05       0  5017.3    0.05       0  5023.5    0.05       0
Bank Sta=5017.3,5023.5
Exp/Cntr=0.3,0.1

Type RM Length L Ch R = 1,17699,446,446,446
BEGIN DESCRIPTION:
Deadman 66 28.0
END DESCRIPTION:
XS GIS Cut Line= 3
      1650954.99      6851138.02      1650905.00      6851288.00
      1650905.00      6851938.01
#Sta/Elev= 30
  4847.6 1941.85  4850.2 1941.85  4858.1 1940.57  4868.7 1938.21  4879.2 1936.37
  4889.7 1935.07  4900.3 1933.05  4910.8 1931.64  4921.4 1931.13  4931.9 1929.98
  4953.0 1928.57  4974.1 1925.08  4992.0 1921.50  4992.5 1921.00  4997.8 1921.00
  4998.3 1921.50  5003.1 1922.85  5015.7 1923.33  5025.7 1924.57  5045.7 1925.34
  5085.7 1925.86  5125.7 1925.83  5215.7 1928.14  5285.7 1931.01  5355.7 1932.65
  5365.7 1932.47  5385.7 1933.12  5395.7 1933.06  5515.7 1935.15  5655.7 1939.19
#Mann=3,-1,0
  4847.6    0.05       0  4992.0    0.05       0  4998.3    0.05       0
Bank Sta=4992,4998.3
Exp/Cntr=0.3,0.1

Type RM Length L Ch R = 1,17253,178,178,178
BEGIN DESCRIPTION:
Deadman 66 27.0
END DESCRIPTION:
XS GIS Cut Line= 3
      1650605.01      6851037.98      1650505.00      6851238.00
      1650905.02      6852038.04
#Sta/Elev= 30
  4772.3 1935.09  4870.1 1930.60  4898.1 1930.02  4942.8 1927.75  4951.2 1926.35
  4959.6 1923.60  4965.2 1924.32  4973.6 1921.05  4982.0 1918.84  4987.5 1919.80
  4990.0 1918.38  4990.5 1917.88  4995.8 1917.88  4996.3 1918.38  4998.7 1918.38
  5004.3 1919.92  5009.9 1920.66  5040.6 1922.53  5138.5 1923.92  5183.2 1925.07
  5272.6 1925.83  5339.7 1927.06  5384.4 1928.27  5412.4 1929.56  5636.0 1933.68
  5725.4 1935.96  5747.8 1937.10  5786.9 1938.15  5831.7 1940.49  5890.4 1942.38
#Mann=3,-1,0
  4772.3    0.05       0  4990.0    0.05       0  4996.3    0.05       0
Bank Sta=4990,4996.3
Exp/Cntr=0.3,0.1