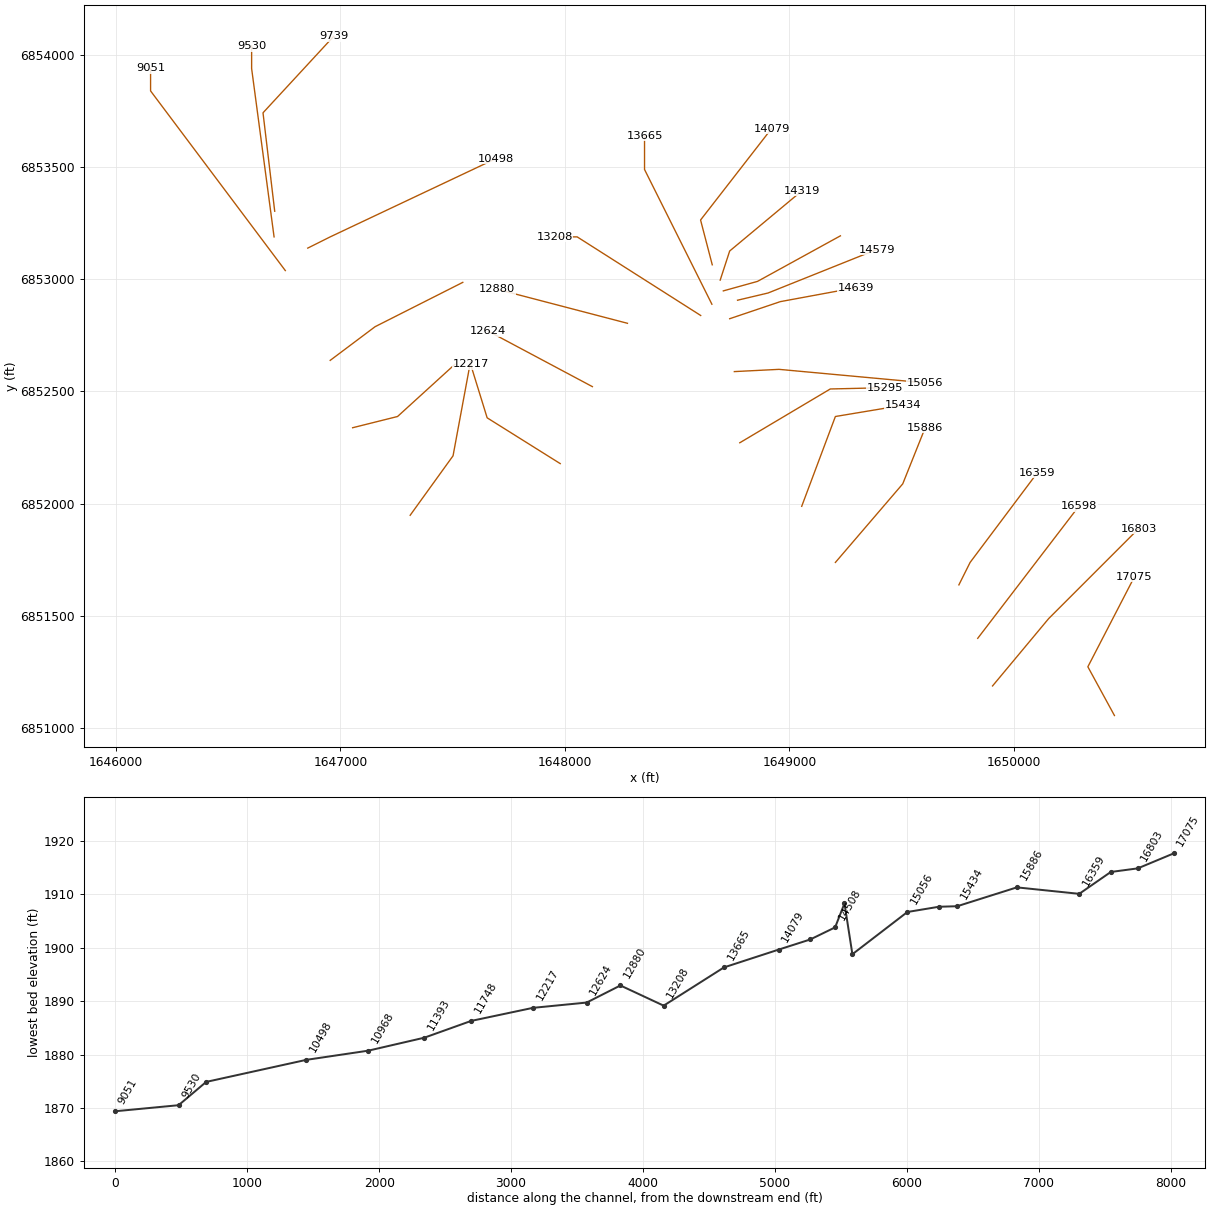
HEC-RAS study Deadman 66.prj: Deadman 66 Base Level Engineering

--- Deadman 66.g01 (geometry) --- (continued)

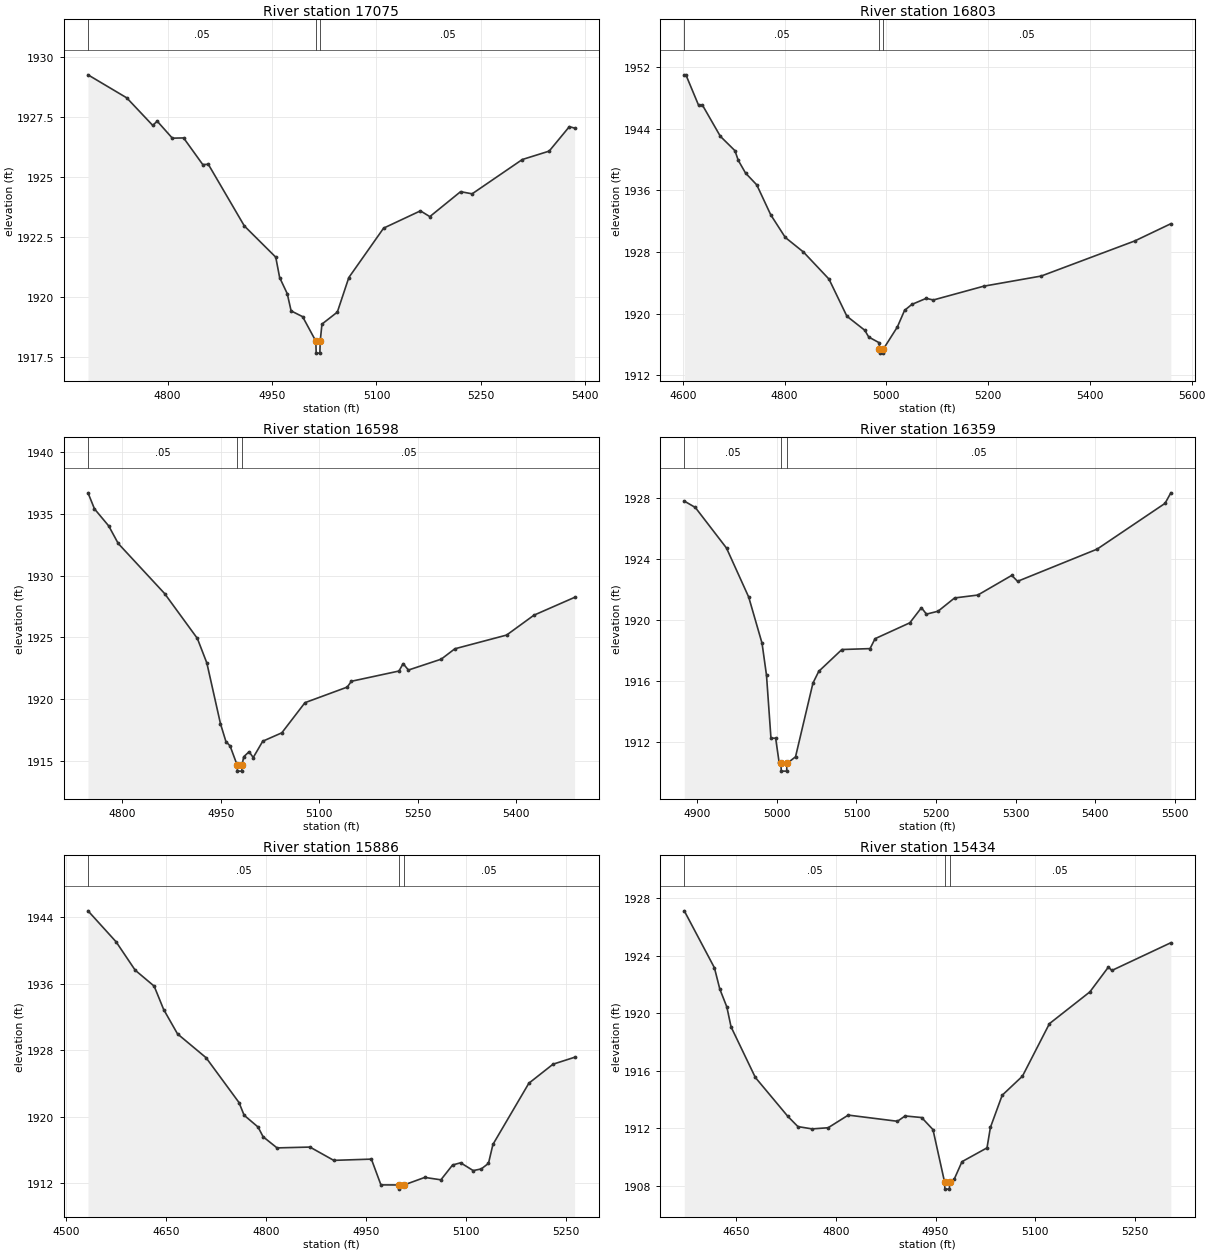
Type RM Length L Ch R = 1,17075,272,272,272
BEGIN DESCRIPTION:
Mapping XS 2114e84d
END DESCRIPTION:
XS GIS Cut Line= 3
      1650447.85      6851056.23      1650329.47      6851273.26
      1650537.20      6851674.68
#Sta/Elev= 30
  4685.5 1929.26  4741.2 1928.30  4778.6 1927.15  4784.9 1927.33  4806.7 1926.62
  4822.9 1926.63  4850.4 1925.52  4858.4 1925.53  4910.2 1922.96  4955.3 1921.66
  4960.9 1920.81  4971.8 1920.14  4977.4 1919.42  4993.9 1919.18  5012.9 1918.16
  5013.4 1917.66  5018.7 1917.66  5019.2 1918.16  5021.7 1918.87  5043.8 1919.37
  5060.3 1920.81  5110.3 1922.87  5163.2 1923.59  5176.7 1923.35  5220.9 1924.39
  5237.5 1924.30  5309.6 1925.73  5348.2 1926.08  5377.2 1927.10  5384.7 1927.04
#Mann=3,-1,0
  4685.5    0.05       0  5012.9    0.05       0  5019.2    0.05       0
Bank Sta=5012.9,5019.2
Exp/Cntr=0.3,0.1

Type RM Length L Ch R = 1,16803,205,205,205
BEGIN DESCRIPTION:
Deadman 66 26.0
END DESCRIPTION:
XS GIS Cut Line= 3
      1649905.01      6851188.01      1650155.00      6851488.00
      1650555.01      6851888.01
#Sta/Elev= 30
  4602.9 1950.99  4606.1 1950.99  4630.9 1947.06  4638.7 1947.05  4673.8 1943.01
  4702.5 1941.14  4709.0 1939.89  4723.3 1938.24  4745.4 1936.70  4772.8 1932.82
  4801.4 1929.88  4837.2 1927.98  4887.3 1924.47  4922.5 1919.65  4957.6 1917.83
  4965.4 1916.95  4986.2 1916.20  4986.3 1915.36  4986.8 1914.86  4993.4 1914.86
  4993.9 1915.36  5021.7 1918.26  5035.8 1920.41  5050.0 1921.18  5078.3 1921.97
  5092.4 1921.76  5191.4 1923.55  5304.5 1924.87  5488.4 1929.43  5559.1 1931.66
#Mann=3,-1,0
  4602.9    0.05       0  4986.3    0.05       0  4993.9    0.05       0
Bank Sta=4986.3,4993.9
Exp/Cntr=0.3,0.1

Type RM Length L Ch R = 1,16598,239,239,239
BEGIN DESCRIPTION:
Mapping XS bff64843
END DESCRIPTION:
XS GIS Cut Line= 2
      1649839.06      6851400.12      1650289.98      6851989.14
#Sta/Elev= 30
  4747.5 1936.70  4757.4 1935.40  4779.1 1934.02  4793.6 1932.60  4864.3 1928.55
  4914.2 1924.92  4928.7 1922.93  4949.5 1918.01  4957.8 1916.57  4964.1 1916.22
  4974.8 1914.68  4975.3 1914.18  4981.9 1914.18  4982.4 1914.68  4984.9 1915.34
  4993.1 1915.75  4999.4 1915.28  5013.9 1916.60  5043.0 1917.28  5078.3 1919.72
  5142.7 1920.98  5149.0 1921.45  5221.6 1922.28  5227.9 1922.88  5236.0 1922.36
  5286.0 1923.24  5306.8 1924.08  5385.7 1925.19  5427.4 1926.80  5489.3 1928.24
#Mann=3,-1,0
  4747.5    0.05       0  4974.8    0.05       0  4982.4    0.05       0
Bank Sta=4974.8,4982.4
Exp/Cntr=0.3,0.1

Type RM Length L Ch R = 1,16359,473,473,473
BEGIN DESCRIPTION:
Deadman 66 25.0
END DESCRIPTION:
XS GIS Cut Line= 3
      1649755.02      6851638.04      1649805.00      6851738.00
      1650105.02      6852138.03
#Sta/Elev= 30
  4883.5 1927.79  4897.4 1927.37  4936.6 1924.71  4964.5 1921.50  4981.3 1918.47
  4986.9 1916.37  4992.5 1912.25  4998.4 1912.25  5002.6 1910.72  5005.0 1910.59
  5005.5 1910.09  5012.2 1910.09  5012.7 1910.59  5023.4 1911.03  5045.3 1915.86
  5052.6 1916.63  5081.7 1918.06  5117.1 1918.12  5123.4 1918.77  5167.1 1919.81
  5181.7 1920.80  5188.0 1920.38  5202.6 1920.57  5223.4 1921.44  5252.6 1921.63
  5295.3 1922.92  5302.6 1922.53  5402.6 1924.64  5488.0 1927.64  5495.3 1928.33
#Mann=3,-1,0
  4883.5    0.05       0  5005.0    0.05       0  5012.7    0.05       0
Bank Sta=5005,5012.7
Exp/Cntr=0.3,0.1

Type RM Length L Ch R = 1,15886,452,452,452
BEGIN DESCRIPTION:
Deadman 66 24.0
END DESCRIPTION:
XS GIS Cut Line= 3
      1649205.01      6851738.02      1649505.00      6852088.00
      1649604.99      6852337.99
#Sta/Elev= 30
  4532.3 1944.78  4574.5 1941.05  4603.1 1937.64  4631.6 1935.72  4645.9 1932.90
  4666.7 1929.97  4709.5 1927.11  4758.9 1921.72  4766.6 1920.19  4787.5 1918.77
  4795.1 1917.60  4816.0 1916.26  4865.4 1916.36  4901.1 1914.76  4957.6 1914.91
  4971.9 1911.81  4998.8 1911.80  4999.3 1911.30  5006.5 1911.80  5037.7 1912.71
  5061.9 1912.42  5079.4 1914.20  5091.5 1914.47  5110.4 1913.53  5122.5 1913.73
  5133.3 1914.40  5140.0 1916.68  5193.9 1924.04  5230.2 1926.33  5262.5 1927.16
#Mann=3,-1,0
  4532.3    0.05       0  4998.8    0.05       0  5006.5    0.05       0
Bank Sta=4998.8,5006.5
Exp/Cntr=0.3,0.1

Type RM Length L Ch R = 1,15434,139,139,139
BEGIN DESCRIPTION:
Deadman 66 23.0
END DESCRIPTION:
XS GIS Cut Line= 3
      1649055.02      6851988.04      1649205.00      6852388.00
      1649505.01      6852438.00
#Sta/Elev= 30
  4572.3 1927.13  4617.6 1923.17  4625.7 1921.69  4636.3 1920.44  4642.6 1919.06
  4679.1 1915.54  4728.0 1912.83  4743.1 1912.12  4764.5 1911.96  4788.5 1912.04
  4818.8 1912.92  4892.7 1912.49  4904.2 1912.86  4929.1 1912.75  4946.1 1911.91
  4963.5 1908.27  4964.0 1907.77  4970.8 1907.77  4971.3 1908.27  4978.1 1908.47
  4989.7 1909.68  5027.3 1910.64  5032.4 1912.06  5050.1 1914.30  5080.6 1915.63
  5121.1 1919.28  5181.9 1921.49  5209.8 1923.22  5214.9 1922.98  5303.6 1924.91
#Mann=3,-1,0
  4572.3    0.05       0  4963.5    0.05       0  4971.3    0.05       0
Bank Sta=4963.5,4971.3
Exp/Cntr=0.3,0.1

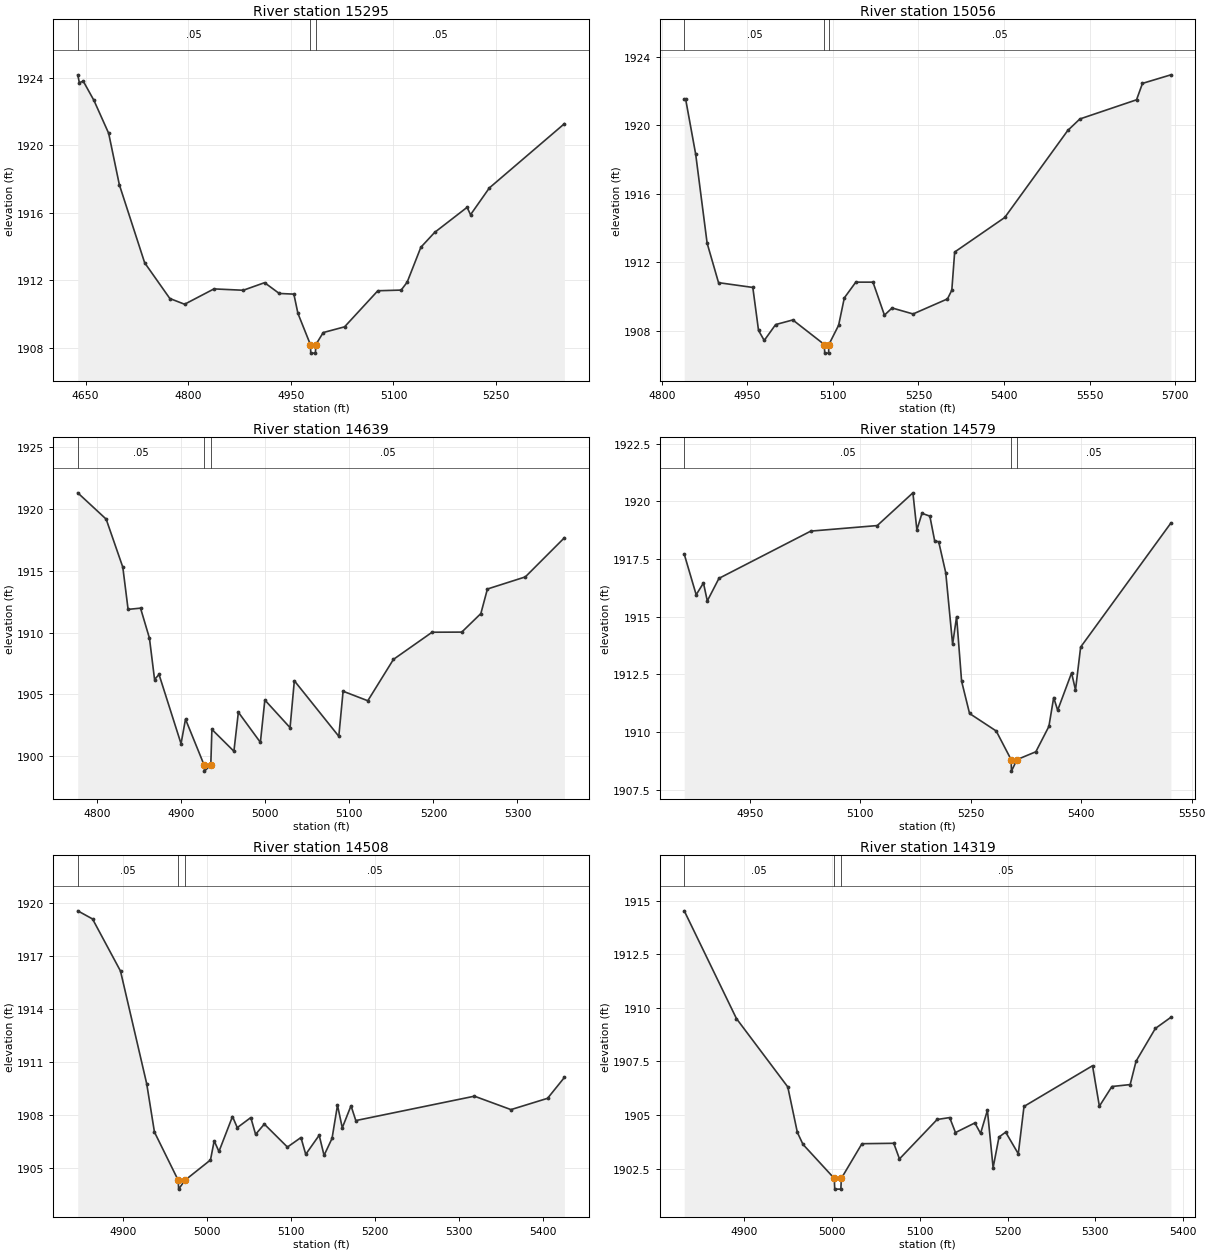
Type RM Length L Ch R = 1,15295,239,239,239
BEGIN DESCRIPTION:
Mapping XS 940555a8
END DESCRIPTION:
XS GIS Cut Line= 3
      1648779.29      6852271.04      1649182.32      6852510.61
      1649424.70      6852516.25
#Sta/Elev= 30
  4638.5 1924.18  4640.8 1923.72  4646.6 1923.80  4662.2 1922.66  4683.7 1920.71
  4699.3 1917.66  4736.3 1913.03  4773.1 1910.91  4794.7 1910.57  4837.6 1911.48
  4880.4 1911.40  4911.6 1911.85  4933.0 1911.21  4954.4 1911.17  4960.3 1910.03
  4978.6 1908.17  4979.1 1907.67  4985.9 1907.67  4986.4 1908.17  4997.3 1908.89
  5028.5 1909.23  5077.1 1911.37  5111.2 1911.41  5120.0 1911.88  5140.0 1913.95
  5160.1 1914.83  5207.6 1916.32  5212.6 1915.88  5240.1 1917.47  5349.8 1921.28
#Mann=3,-1,0
  4638.5    0.05       0  4978.6    0.05       0  4986.4    0.05       0
Bank Sta=4978.6,4986.4
Exp/Cntr=0.3,0.1

Type RM Length L Ch R = 1,15056,417,417,417
BEGIN DESCRIPTION:
Deadman 66 22.0
END DESCRIPTION:
XS GIS Cut Line= 3
      1648754.96      6852588.00      1648954.02      6852597.99
      1649604.95      6852538.00
#Sta/Elev= 30
  4839.4 1921.53  4841.9 1921.53  4859.5 1918.31  4879.5 1913.12  4899.5 1910.81
  4959.6 1910.53  4969.6 1908.02  4979.6 1907.43  4999.6 1908.36  5029.7 1908.63
  5085.1 1907.19  5085.6 1906.69  5092.4 1906.69  5092.9 1907.19  5110.0 1908.32
  5120.0 1909.92  5140.1 1910.84  5170.2 1910.84  5190.3 1908.91  5203.7 1909.33
  5240.5 1908.98  5300.8 1909.86  5308.4 1910.37  5313.4 1912.60  5401.2 1914.62
  5511.7 1919.71  5532.9 1920.38  5632.2 1921.50  5642.6 1922.46  5692.4 1922.96
#Mann=3,-1,0
  4839.4    0.05       0  5085.1    0.05       0  5092.9    0.05       0
Bank Sta=5085.1,5092.9
Exp/Cntr=0.3,0.1

Type RM Length L Ch R = 1,14639,60,60,60
BEGIN DESCRIPTION:
Mapping XS aabedb1a
END DESCRIPTION:
XS GIS Cut Line= 3
      1648734.22      6852823.49      1648959.65      6852899.57
      1649295.04      6852961.58
#Sta/Elev= 30
  4776.8 1921.32  4810.6 1919.19  4830.4 1915.30  4836.7 1911.88  4851.5 1911.98
  4862.1 1909.55  4868.2 1906.20  4873.5 1906.61  4899.7 1901.00  4905.0 1902.99
  4927.1 1899.28  4927.6 1898.78  4935.1 1899.28  4936.4 1902.16  4962.6 1900.39
  4967.9 1903.55  4994.1 1901.11  4999.4 1904.54  5029.4 1902.30  5034.5 1906.10
  5087.4 1901.60  5092.5 1905.25  5121.9 1904.48  5152.4 1907.83  5198.4 1910.03
  5233.7 1910.04  5256.4 1911.54  5264.2 1913.53  5309.3 1914.51  5355.8 1917.68
#Mann=3,-1,0
  4776.8    0.05       0  4927.1    0.05       0  4935.1    0.05       0
Bank Sta=4927.1,4935.1
Exp/Cntr=0.3,0.1

Type RM Length L Ch R = 1,14579,71,71,71
BEGIN DESCRIPTION:
Deadman 66 21.0
END DESCRIPTION:
XS GIS Cut Line= 3
      1648769.21      6852905.90      1648905.00      6852938.00
      1649388.73      6853131.70
#Sta/Elev= 30
  4861.2 1917.71  4877.4 1915.95  4887.3 1916.46  4892.5 1915.68  4908.3 1916.66
  5033.0 1918.71  5123.2 1918.95  5171.6 1920.37  5177.0 1918.76  5183.9 1919.48
  5194.6 1919.36  5201.2 1918.28  5206.6 1918.25  5216.2 1916.90  5225.5 1913.80
  5230.9 1915.00  5237.7 1912.20  5248.5 1910.80  5284.7 1910.04  5304.9 1908.80
  5305.4 1908.30  5312.9 1908.80  5338.5 1909.14  5356.2 1910.24  5362.7 1911.49
  5368.1 1910.94  5387.0 1912.56  5392.3 1911.82  5399.3 1913.68  5521.8 1919.06
#Mann=3,-1,0
  4861.2    0.05       0  5304.9    0.05       0  5312.9    0.05       0
Bank Sta=5304.9,5312.9
Exp/Cntr=0.3,0.1

Type RM Length L Ch R = 1,14508,189,189,189
BEGIN DESCRIPTION:
Mapping XS 3d020697
END DESCRIPTION:
XS GIS Cut Line= 3
      1648705.94      6852947.48      1648858.19      6852989.77
      1649227.39      6853192.69
#Sta/Elev= 30
  4846.5 1919.56  4864.1 1919.10  4897.4 1916.15  4928.6 1909.77  4937.8 1907.04
  4966.1 1904.31  4966.6 1903.81  4974.1 1904.31  5004.5 1905.46  5008.9 1906.54
  5014.6 1905.94  5030.7 1907.92  5036.4 1907.29  5052.5 1907.86  5058.2 1906.91
  5068.6 1907.49  5096.1 1906.19  5112.2 1906.73  5117.9 1905.78  5133.9 1906.86
  5139.7 1905.72  5149.2 1906.68  5155.7 1908.56  5161.4 1907.28  5171.8 1908.53
  5177.5 1907.69  5318.7 1909.07  5362.2 1908.31  5405.8 1908.95  5425.8 1910.13
#Mann=3,-1,0
  4846.5    0.05       0  4966.1    0.05       0  4974.1    0.05       0
Bank Sta=4966.1,4974.1
Exp/Cntr=0.3,0.1

Type RM Length L Ch R = 1,14319,240,240,240
BEGIN DESCRIPTION:
Mapping XS 46de2513
END DESCRIPTION:
XS GIS Cut Line= 3
      1648691.90      6852995.43      1648734.17      6853125.06
      1649055.48      6853392.82
#Sta/Elev= 30
  4831.5 1914.53  4891.0 1909.50  4949.5 1906.31  4960.4 1904.19  4966.8 1903.63
  5002.5 1902.04  5003.0 1901.54  5010.0 1901.54  5010.5 1902.04  5034.0 1903.66
  5070.3 1903.68  5076.8 1902.95  5119.7 1904.79  5134.0 1904.88  5140.6 1904.18
  5162.7 1904.63  5169.2 1904.14  5177.0 1905.22  5183.5 1902.54  5190.2 1903.97
  5197.8 1904.20  5212.2 1903.19  5218.7 1905.40  5296.8 1907.30  5304.6 1905.41
  5318.9 1906.33  5339.7 1906.42  5346.4 1907.51  5368.4 1909.04  5386.1 1909.56
#Mann=3,-1,0
  4831.5    0.05       0  5002.5    0.05       0  5010.5    0.05       0
Bank Sta=5002.5,5010.5
Exp/Cntr=0.3,0.1

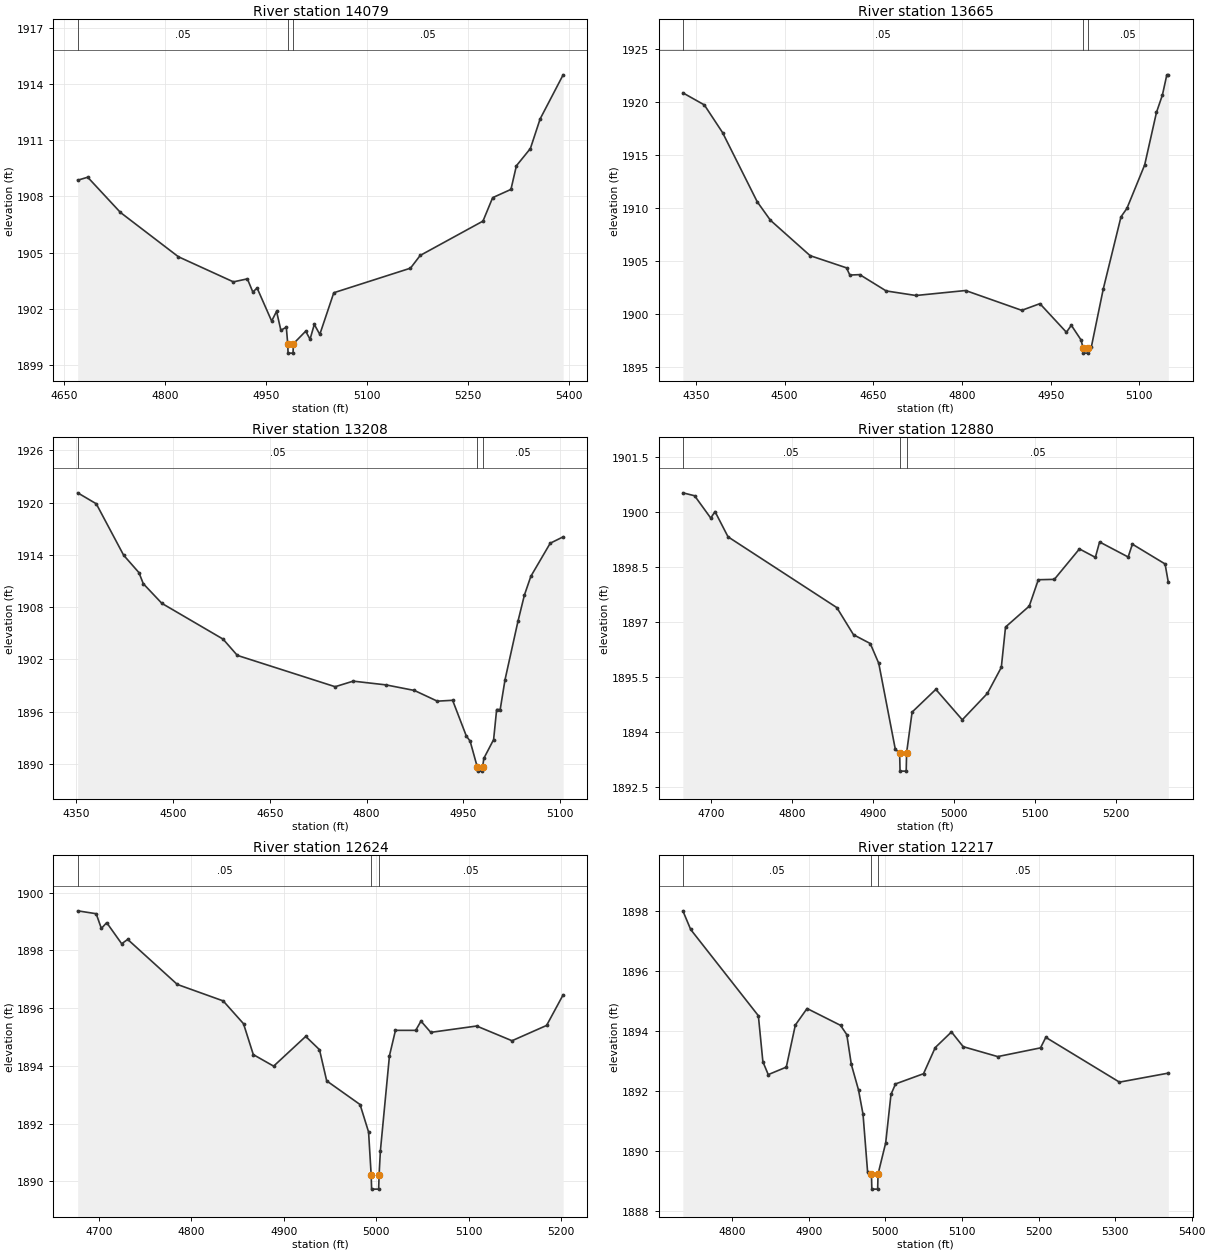
Type RM Length L Ch R = 1,14079,414,414,414
BEGIN DESCRIPTION:
Mapping XS 03d03628
END DESCRIPTION:
XS GIS Cut Line= 3
      1648656.61      6853063.55      1648604.53      6853263.19
      1648920.70      6853670.32
#Sta/Elev= 30
  4669.8 1908.86  4684.7 1909.02  4733.4 1907.14  4819.5 1904.78  4901.3 1903.44
  4922.1 1903.60  4930.2 1902.90  4936.6 1903.11  4958.2 1901.35  4965.5 1901.87
  4971.9 1900.86  4980.0 1901.02  4982.1 1900.14  4982.6 1899.64  4990.0 1899.64
  4990.5 1900.14  5008.8 1900.81  5015.3 1900.38  5021.6 1901.17  5029.8 1900.64
  5050.6 1902.86  5164.6 1904.17  5179.1 1904.85  5272.4 1906.68  5286.8 1907.93
  5314.0 1908.37  5322.1 1909.63  5342.9 1910.55  5357.4 1912.13  5391.6 1914.48
#Mann=3,-1,0
  4669.8    0.05       0  4982.1    0.05       0  4990.5    0.05       0
Bank Sta=4982.1,4990.5
Exp/Cntr=0.3,0.1

Type RM Length L Ch R = 1,13665,457,457,457
BEGIN DESCRIPTION:
Deadman 66 20.0
END DESCRIPTION:
XS GIS Cut Line= 3
      1648655.00      6852888.00      1648355.00      6853488.00
      1648355.00      6853637.98
#Sta/Elev= 30
  4328.1 1920.88  4364.4 1919.74  4395.2 1917.13  4453.9 1910.59  4476.2 1908.85
  4543.3 1905.51  4604.8 1904.36  4610.4 1903.68  4627.2 1903.72  4671.9 1902.18
  4722.2 1901.75  4806.1 1902.22  4901.1 1900.35  4931.8 1900.98  4976.6 1898.28
  4984.9 1898.94  5001.4 1897.55  5004.7 1896.81  5005.2 1896.31  5012.7 1896.31
  5013.2 1896.81  5018.9 1896.93  5038.9 1902.36  5068.9 1909.18  5078.9 1909.97
  5108.9 1914.07  5128.9 1919.04  5138.9 1920.67  5146.4 1922.58  5148.9 1922.58
#Mann=3,-1,0
  4328.1    0.05       0  5004.7    0.05       0  5013.2    0.05       0
Bank Sta=5004.7,5013.2
Exp/Cntr=0.3,0.1

Type RM Length L Ch R = 1,13208,328,328,328
BEGIN DESCRIPTION:
Deadman 66 19.0
END DESCRIPTION:
XS GIS Cut Line= 3
      1648605.03      6852837.98      1648055.00      6853188.00
      1647954.96      6853188.00
#Sta/Elev= 30
  4352.4 1921.13  4381.2 1919.87  4423.6 1913.96  4447.3 1911.96  4454.0 1910.69
  4482.8 1908.43  4577.6 1904.32  4599.7 1902.45  4751.2 1898.85  4779.2 1899.49
  4830.0 1899.06  4874.0 1898.42  4909.5 1897.19  4933.2 1897.29  4954.4 1893.19
  4960.3 1892.60  4971.3 1889.65  4971.8 1889.15  4979.3 1889.15  4979.8 1889.65
  4981.5 1890.61  4996.7 1892.77  5001.4 1896.23  5006.9 1896.23  5014.4 1899.66
  5034.4 1906.36  5044.4 1909.38  5054.4 1911.54  5084.4 1915.34  5104.4 1916.07
#Mann=3,-1,0
  4352.4    0.05       0  4971.3    0.05       0  4979.8    0.05       0
Bank Sta=4971.3,4979.8
Exp/Cntr=0.3,0.1

Type RM Length L Ch R = 1,12880,256,256,256
BEGIN DESCRIPTION:
Mapping XS 3c58f313
END DESCRIPTION:
XS GIS Cut Line= 2
      1648278.98      6852803.13      1647698.75      6852954.68
#Sta/Elev= 30
  4665.2 1900.52  4679.7 1900.44  4699.7 1899.83  4704.9 1900.01  4721.0 1899.32
  4855.4 1897.39  4876.0 1896.65  4896.7 1896.41  4907.2 1895.87  4927.7 1893.52
  4933.0 1893.43  4933.5 1892.93  4941.1 1892.93  4941.6 1893.43  4948.4 1894.54
  4977.7 1895.16  5010.4 1894.33  5041.4 1895.05  5058.6 1895.76  5063.8 1896.86
  5093.1 1897.43  5104.3 1898.15  5124.1 1898.16  5155.1 1898.99  5174.8 1898.76
  5180.0 1899.18  5215.3 1898.77  5220.5 1899.12  5260.9 1898.58  5264.9 1898.08
#Mann=3,-1,0
  4665.2    0.05       0  4933.0    0.05       0  4941.6    0.05       0
Bank Sta=4933,4941.6
Exp/Cntr=0.3,0.1

Type RM Length L Ch R = 1,12624,407,407,407
BEGIN DESCRIPTION:
Mapping XS d07c8e11
END DESCRIPTION:
XS GIS Cut Line= 2
      1648122.73      6852521.02      1647659.20      6852767.95
#Sta/Elev= 30
  4676.9 1899.37  4696.9 1899.27  4702.5 1898.76  4708.3 1898.96  4724.5 1898.23
  4731.0 1898.38  4784.7 1896.82  4834.3 1896.25  4856.3 1895.46  4866.9 1894.39
  4888.9 1893.99  4923.6 1895.02  4938.5 1894.56  4946.3 1893.48  4982.4 1892.66
  4991.6 1891.71  4994.4 1890.23  4994.9 1889.73  5002.5 1889.73  5003.0 1890.23
  5004.4 1891.06  5014.2 1894.35  5020.7 1895.23  5042.6 1895.23  5048.3 1895.55
  5058.9 1895.16  5108.5 1895.38  5146.8 1894.87  5184.2 1895.40  5202.1 1896.46
#Mann=3,-1,0
  4676.9    0.05       0  4994.4    0.05       0  5003.0    0.05       0
Bank Sta=4994.4,5003
Exp/Cntr=0.3,0.1

Type RM Length L Ch R = 1,12217,469,469,469
BEGIN DESCRIPTION:
Mapping XS 8784857a
END DESCRIPTION:
XS GIS Cut Line= 3
      1647979.50      6852178.14      1647654.01      6852382.12
      1647580.22      6852620.85
#Sta/Elev= 30
  4735.5 1898.00  4745.7 1897.38  4834.1 1894.51  4840.0 1892.98  4847.0 1892.55
  4870.6 1892.80  4882.4 1894.20  4897.7 1894.75  4941.4 1894.19  4949.6 1893.88
  4955.5 1892.89  4964.9 1892.04  4970.8 1891.23  4976.8 1889.30  4981.8 1889.24
  4982.3 1888.74  4989.9 1888.74  4990.4 1889.24  5000.4 1890.28  5007.3 1891.89
  5013.2 1892.24  5049.8 1892.58  5065.1 1893.45  5086.3 1893.97  5101.6 1893.48
  5146.7 1893.15  5202.6 1893.44  5209.5 1893.79  5305.7 1892.30  5369.5 1892.60
#Mann=3,-1,0
  4735.5    0.05       0  4981.8    0.05       0  4990.4    0.05       0
Bank Sta=4981.8,4990.4
Exp/Cntr=0.3,0.1

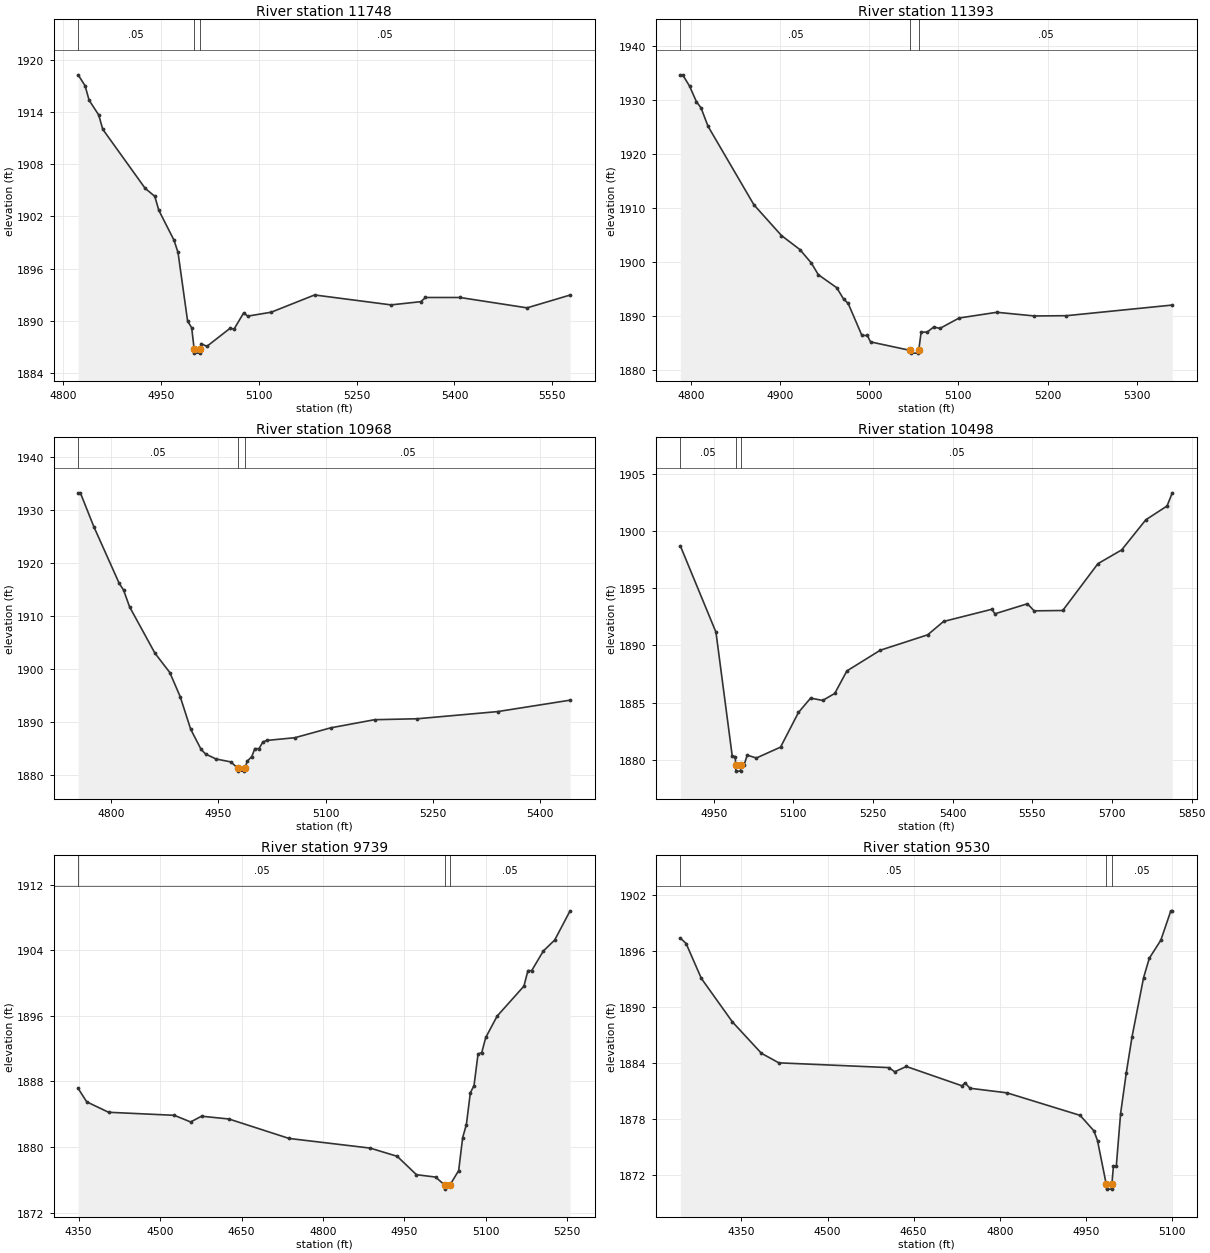
Type RM Length L Ch R = 1,11748,355,355,355
BEGIN DESCRIPTION:
Mapping XS e579e656
END DESCRIPTION:
XS GIS Cut Line= 3
      1647311.12      6851948.07      1647502.10      6852212.85
      1647580.03      6852632.81
#Sta/Elev= 30
  4823.5 1918.25  4834.1 1917.00  4840.3 1915.34  4855.0 1913.64  4861.2 1912.00
  4926.2 1905.21  4940.9 1904.30  4947.1 1902.69  4970.3 1899.27  4976.5 1897.85
  4991.2 1889.96  4997.4 1889.21  5001.2 1886.79  5001.7 1886.29  5010.1 1886.29
  5010.6 1886.79  5012.1 1887.38  5020.6 1887.06  5056.2 1889.14  5062.4 1889.06
  5077.1 1890.91  5083.3 1890.54  5119.3 1890.99  5185.7 1892.97  5302.8 1891.83
  5348.5 1892.20  5355.6 1892.68  5408.4 1892.68  5511.2 1891.49  5577.1 1892.96
#Mann=3,-1,0
  4823.5    0.05       0  5001.2    0.05       0  5010.6    0.05       0
Bank Sta=5001.2,5010.6
Exp/Cntr=0.3,0.1

Type RM Length L Ch R = 1,11393,425,425,425
BEGIN DESCRIPTION:
Deadman 66 18.0
END DESCRIPTION:
XS GIS Cut Line= 3
      1647054.96      6852337.99      1647255.00      6852388.00
      1647510.43      6852620.51
#Sta/Elev= 30
  4788.3 1934.67  4790.9 1934.67  4798.6 1932.60  4806.4 1929.67  4811.5 1928.56
  4819.3 1925.16  4870.8 1910.61  4901.7 1904.92  4922.3 1902.33  4935.2 1899.83
  4943.0 1897.67  4963.6 1895.27  4971.3 1893.18  4976.5 1892.35  4991.9 1886.42
  4997.9 1886.42  5001.6 1885.23  5046.2 1883.65  5046.7 1883.15  5055.1 1883.15
  5055.6 1883.65  5058.3 1887.04  5065.1 1887.05  5072.5 1888.00  5079.3 1887.72
  5100.9 1889.65  5143.2 1890.71  5185.4 1890.03  5221.2 1890.08  5339.9 1892.05
#Mann=3,-1,0
  4788.3    0.05       0  5046.2    0.05       0  5055.6    0.05       0
Bank Sta=5046.2,5055.6
Exp/Cntr=0.3,0.1

Type RM Length L Ch R = 1,10968,470,470,470
BEGIN DESCRIPTION:
Deadman 66 17.0
END DESCRIPTION:
XS GIS Cut Line= 3
      1646955.02      6852638.01      1647155.00      6852788.00
      1647545.46      6852985.39
#Sta/Elev= 30
  4754.3 1933.27  4757.4 1933.27  4776.2 1926.89  4811.6 1916.20  4817.8 1914.91
  4826.2 1911.74  4861.6 1903.00  4882.4 1899.34  4897.0 1894.76  4911.6 1888.63
  4926.2 1884.81  4932.4 1883.96  4947.0 1883.01  4967.8 1882.46  4977.7 1881.22
  4978.2 1880.72  4986.7 1880.72  4987.2 1881.22  4990.7 1882.61  4997.0 1883.48
  5001.2 1884.97  5007.1 1884.97  5012.6 1886.25  5018.2 1886.52  5057.2 1887.03
  5107.4 1888.90  5168.6 1890.43  5228.4 1890.61  5340.4 1891.96  5441.8 1894.12
#Mann=3,-1,0
  4754.3    0.05       0  4977.7    0.05       0  4987.2    0.05       0
Bank Sta=4977.7,4987.2
Exp/Cntr=0.3,0.1

Type RM Length L Ch R = 1,10498,759,759,759
BEGIN DESCRIPTION:
Deadman 66 16.0
END DESCRIPTION:
XS GIS Cut Line= 3
      1646855.01      6853138.00      1646955.00      6853188.00
      1647691.57      6853535.92
#Sta/Elev= 30
  4887.1 1898.72  4954.2 1891.16  4984.9 1880.30  4990.5 1880.28  4991.3 1879.50
  4991.8 1879.00  5000.4 1879.00  5000.9 1879.50  5007.5 1879.58  5013.0 1880.40
  5030.3 1880.15  5075.8 1881.10  5109.6 1884.14  5132.4 1885.39  5155.2 1885.19
  5177.9 1885.80  5200.7 1887.77  5263.5 1889.58  5352.8 1890.93  5382.8 1892.10
  5473.9 1893.17  5479.4 1892.77  5540.8 1893.65  5553.3 1893.03  5607.2 1893.06
  5673.5 1897.16  5718.1 1898.36  5763.7 1901.00  5803.7 1902.21  5813.5 1903.36
#Mann=3,-1,0
  4887.1    0.05       0  4991.3    0.05       0  5000.9    0.05       0
Bank Sta=4991.3,5000.9
Exp/Cntr=0.3,0.1

Type RM Length L Ch R = 1,9739,209,209,209
BEGIN DESCRIPTION:
Mapping XS b8e56b35
END DESCRIPTION:
XS GIS Cut Line= 3
      1646707.83      6853302.27      1646655.75      6853740.62
      1646971.03      6854081.82
#Sta/Elev= 30
  4349.0 1887.15  4364.8 1885.51  4405.1 1884.24  4526.0 1883.87  4556.2 1883.06
  4576.3 1883.76  4626.7 1883.42  4737.4 1881.05  4887.0 1879.87  4936.6 1878.87
  4972.1 1876.63  5007.3 1876.34  5024.0 1875.37  5024.5 1874.87  5033.7 1875.37
  5049.8 1877.13  5057.2 1881.16  5064.0 1882.74  5071.3 1886.61  5078.1 1887.50
  5085.5 1891.35  5092.3 1891.52  5099.7 1893.36  5120.7 1895.97  5170.0 1899.62
  5177.4 1901.52  5184.2 1901.50  5205.7 1903.90  5226.7 1905.24  5255.0 1908.80
#Mann=3,-1,0
  4349.0    0.05       0  5024.0    0.05       0  5033.7    0.05       0
Bank Sta=5024,5033.7
Exp/Cntr=0.3,0.1

Type RM Length L Ch R = 1,9530,479,479,479
BEGIN DESCRIPTION:
Deadman 66 15.0
END DESCRIPTION:
XS GIS Cut Line= 3
      1646705.00      6853187.99      1646605.00      6853938.00
      1646605.00      6854037.95
#Sta/Elev= 30
  4243.7 1897.37  4253.8 1896.78  4280.3 1893.05  4334.5 1888.39  4384.9 1885.04
  4415.2 1884.02  4606.9 1883.51  4617.0 1883.06  4637.2 1883.63  4734.3 1881.56
  4739.3 1881.88  4748.1 1881.30  4812.4 1880.81  4939.8 1878.40  4963.8 1876.75
  4970.1 1875.70  4985.4 1871.01  4985.9 1870.51  4994.6 1870.51  4995.1 1871.01
  4997.8 1872.95  5002.8 1872.95  5010.3 1878.59  5020.3 1882.98  5030.3 1886.83
  5050.3 1893.12  5060.3 1895.21  5080.3 1897.13  5097.8 1900.28  5100.3 1900.28
#Mann=3,-1,0
  4243.7    0.05       0  4985.4    0.05       0  4995.1    0.05       0
Bank Sta=4985.4,4995.1
Exp/Cntr=0.3,0.1

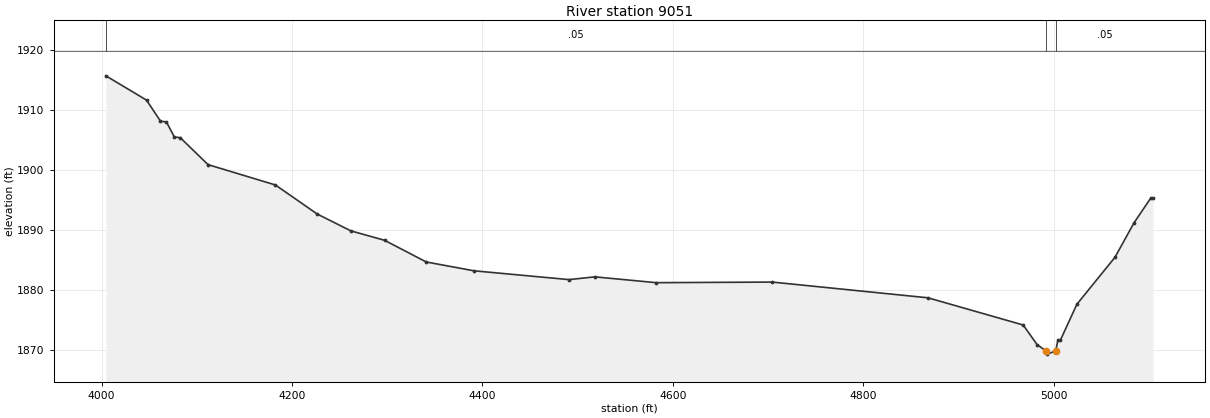
Type RM Length L Ch R = 1,9051,521,521,521
BEGIN DESCRIPTION:
Deadman 66 14.0
END DESCRIPTION:
XS GIS Cut Line= 3
      1646755.01      6853037.99      1646155.00      6853838.00
      1646155.00      6853937.99
#Sta/Elev= 30
  4004.5 1915.73  4047.2 1911.68  4061.8 1908.19  4068.1 1908.04  4076.4 1905.54
  4082.6 1905.43  4111.8 1900.94  4182.6 1897.55  4226.4 1892.72  4261.8 1889.91
  4297.2 1888.34  4341.0 1884.73  4391.0 1883.26  4491.0 1881.79  4518.1 1882.25
  4582.6 1881.28  4704.5 1881.38  4868.1 1878.76  4968.1 1874.23  4982.6 1870.98
  4992.4 1869.88  4992.9 1869.38  5002.1 1869.88  5004.5 1871.65  5007.0 1871.65
  5024.5 1877.69  5064.5 1885.51  5084.5 1891.25  5102.0 1895.35  5104.5 1895.35
#Mann=3,-1,0
  4004.5    0.05       0  4992.4    0.05       0  5002.1    0.05       0
Bank Sta=4992.4,5002.1
Exp/Cntr=0.3,0.1