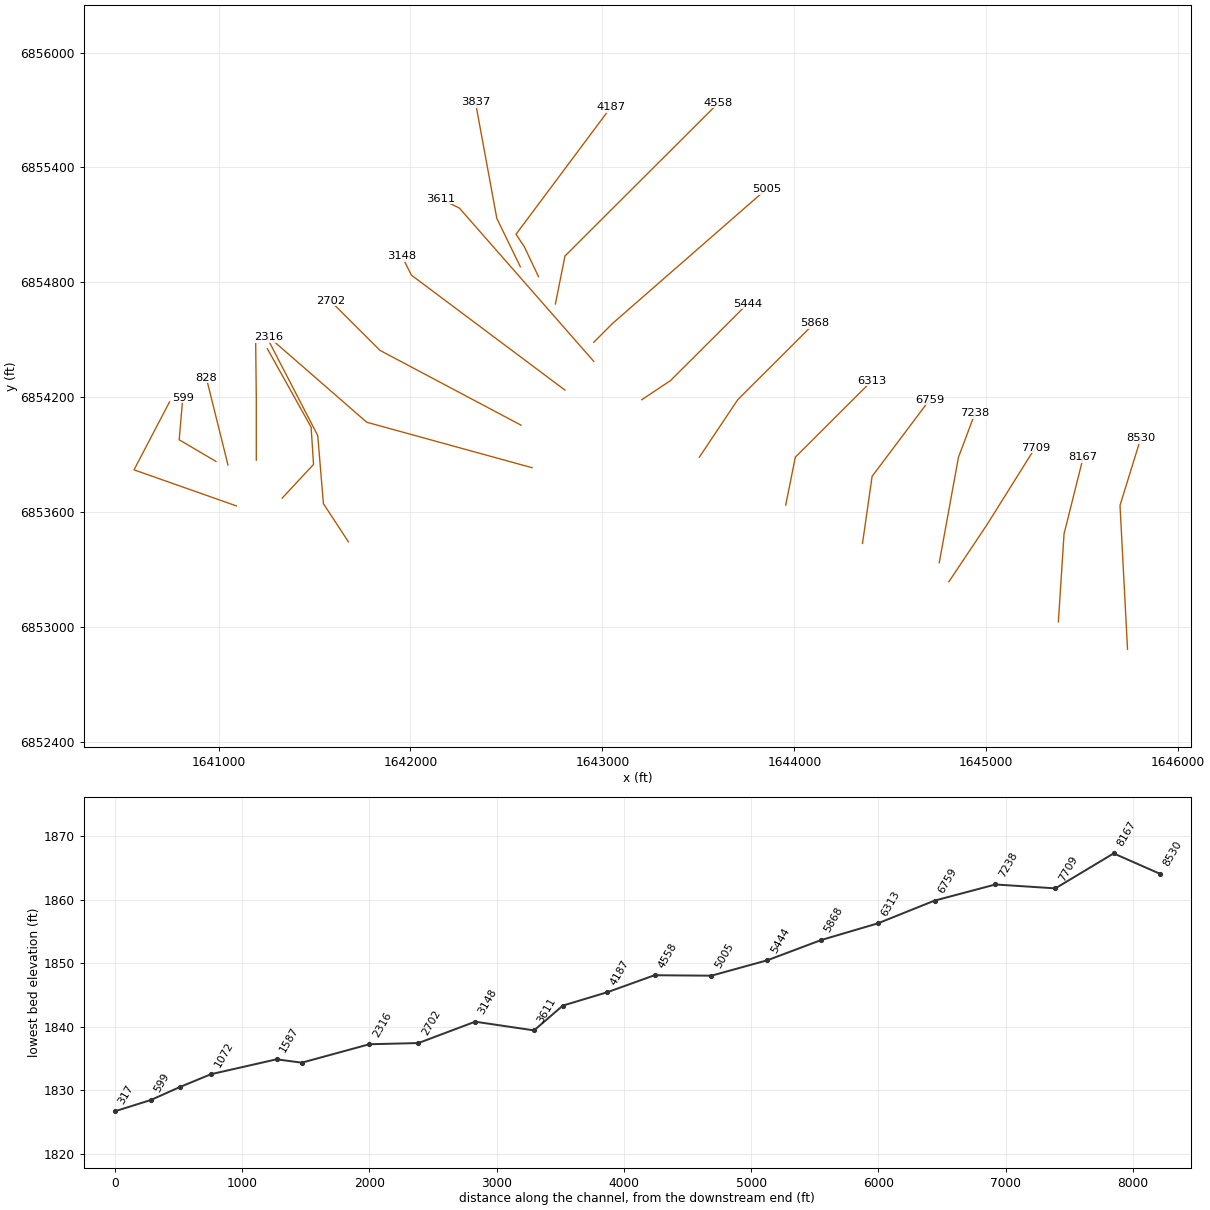
HEC-RAS study Deadman 66.prj: Deadman 66 Base Level Engineering

--- Deadman 66.g01 (geometry) --- (continued)

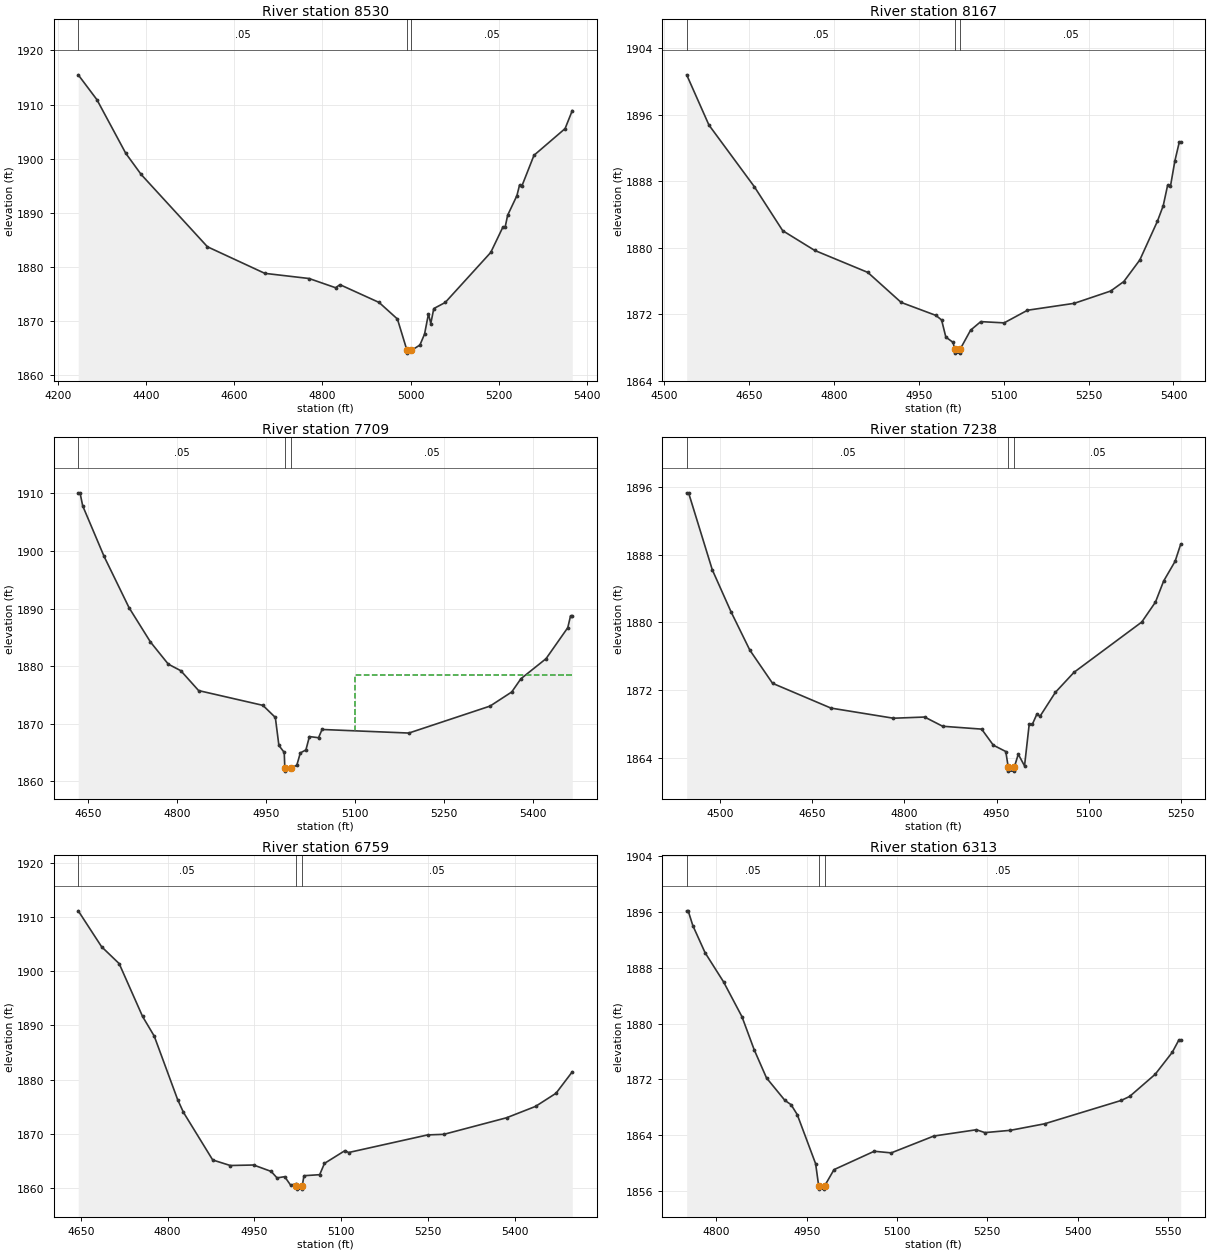
Type RM Length L Ch R = 1,8530,363,363,363
BEGIN DESCRIPTION:
Deadman 66 13.0
END DESCRIPTION:
XS GIS Cut Line= 3
      1645735.61      6852885.63      1645696.55      6853636.46
      1645804.99      6853987.96
#Sta/Elev= 30
  4246.6 1915.49  4289.0 1910.89  4354.3 1901.00  4389.2 1897.09  4539.4 1883.74
  4669.5 1878.83  4769.7 1877.88  4829.8 1876.18  4839.8 1876.74  4928.4 1873.46
  4970.0 1870.40  4991.7 1864.60  4992.2 1864.10  5001.7 1864.60  5021.0 1865.60
  5031.5 1867.62  5040.4 1871.36  5045.6 1869.56  5052.4 1872.33  5078.3 1873.45
  5181.5 1882.69  5208.9 1887.35  5214.1 1887.35  5219.8 1889.56  5240.8 1893.18
  5246.8 1895.14  5252.0 1894.94  5279.5 1900.63  5350.0 1905.56  5366.3 1908.89
#Mann=3,-1,0
  4246.6    0.05       0  4991.7    0.05       0  5001.7    0.05       0
Bank Sta=4991.7,5001.7
Exp/Cntr=0.3,0.1

Type RM Length L Ch R = 1,8167,458,458,458
BEGIN DESCRIPTION:
Deadman 66 12.0
END DESCRIPTION:
XS GIS Cut Line= 3
      1645375.36      6853028.78      1645405.00      6853488.00
      1645505.00      6853888.01
#Sta/Elev= 30
  4540.3 1900.78  4579.6 1894.74  4659.8 1887.32  4709.9 1882.03  4766.3 1879.66
  4860.2 1877.01  4919.1 1873.40  4980.4 1871.84  4990.5 1871.29  4998.0 1869.23
  5010.8 1868.59  5013.5 1867.80  5014.0 1867.30  5023.0 1867.30  5023.5 1867.80
  5041.7 1870.06  5059.7 1871.09  5101.0 1870.94  5142.2 1872.46  5224.7 1873.29
  5289.1 1874.77  5312.3 1875.91  5340.6 1878.51  5371.6 1883.16  5381.9 1885.03
  5389.6 1887.47  5394.7 1887.38  5402.5 1890.43  5410.2 1892.66  5412.8 1892.66
#Mann=3,-1,0
  4540.3    0.05       0  5013.5    0.05       0  5023.5    0.05       0
Bank Sta=5013.5,5023.5
Exp/Cntr=0.3,0.1

Type RM Length L Ch R = 1,7709,471,471,471
BEGIN DESCRIPTION:
Deadman 66 11.0
END DESCRIPTION:
XS GIS Cut Line= 3
      1644805.00      6853238.00      1645005.00      6853538.00
      1645254.97      6853937.96
#Sta/Elev= 30
  4633.5 1910.11  4636.5 1910.11  4641.0 1907.85  4677.1 1899.06  4719.1 1890.17
  4755.2 1884.21  4785.2 1880.37  4806.3 1879.23  4836.3 1875.78  4944.5 1873.22
  4965.5 1871.12  4971.5 1866.26  4980.5 1865.04  4981.5 1862.30  4982.0 1861.80
  4991.6 1862.30  5001.7 1862.83  5007.6 1864.96  5017.0 1865.48  5022.9 1867.80
  5038.3 1867.60  5044.2 1869.03  5190.4 1868.41  5327.2 1873.09  5363.7 1875.54
  5379.1 1877.83  5421.5 1881.32  5458.1 1886.70  5462.8 1888.75  5465.7 1888.75
#Mann=3,-1,0
  4633.5    0.05       0  4981.5    0.05       0  4991.6    0.05       0
#XS Ineff=2,0
       0                 5099.70    0.00 1878.54
Permanent Ineff=
       F       F
Bank Sta=4981.5,4991.6
Exp/Cntr=0.3,0.1

Type RM Length L Ch R = 1,7238,479,479,479
BEGIN DESCRIPTION:
Deadman 66 10.0
END DESCRIPTION:
XS GIS Cut Line= 3
      1644754.70      6853336.97      1644855.00      6853888.00
      1644940.68      6854116.48
#Sta/Elev= 30
  4445.7 1895.34  4448.8 1895.34  4487.4 1886.23  4517.9 1881.26  4548.4 1876.74
  4585.5 1872.80  4680.5 1869.87  4782.2 1868.67  4833.0 1868.81  4862.3 1867.72
  4925.8 1867.38  4944.8 1865.48  4965.1 1864.73  4969.0 1862.91  4969.5 1862.41
  4978.6 1862.41  4979.1 1862.91  4985.4 1864.41  4995.6 1863.03  5003.2 1867.96
  5008.4 1867.96  5015.6 1869.14  5020.9 1868.91  5045.8 1871.73  5076.1 1874.10
  5186.4 1880.05  5208.7 1882.41  5222.0 1884.90  5240.7 1887.24  5249.8 1889.27
#Mann=3,-1,0
  4445.7    0.05       0  4969.0    0.05       0  4979.1    0.05       0
Bank Sta=4969,4979.1
Exp/Cntr=0.3,0.1

Type RM Length L Ch R = 1,6759,446,446,446
BEGIN DESCRIPTION:
Deadman 66 9.0
END DESCRIPTION:
XS GIS Cut Line= 3
      1644355.00      6853438.02      1644405.00      6853788.00
      1644704.98      6854187.97
#Sta/Elev= 30
  4645.7 1911.11  4686.1 1904.49  4716.4 1901.39  4756.8 1891.67  4777.0 1888.04
  4817.4 1876.36  4827.5 1874.00  4878.0 1865.24  4908.3 1864.22  4948.7 1864.31
  4979.0 1863.13  4989.1 1861.94  5002.4 1862.16  5012.8 1860.57  5021.1 1860.86
  5022.3 1860.37  5022.8 1859.87  5032.0 1859.87  5032.5 1860.37  5035.7 1862.34
  5062.8 1862.53  5071.1 1864.61  5106.5 1866.96  5112.8 1866.61  5249.2 1869.85
  5277.4 1869.96  5385.7 1873.01  5435.7 1875.10  5471.1 1877.52  5499.2 1881.47
#Mann=3,-1,0
  4645.7    0.05       0  5022.3    0.03       0  5032.5    0.05       0
Bank Sta=5022.3,5032.5
Exp/Cntr=0.3,0.1

Type RM Length L Ch R = 1,6313,445,445,445
BEGIN DESCRIPTION:
Deadman 66 8.0
END DESCRIPTION:
XS GIS Cut Line= 3
      1643955.00      6853638.01      1644005.00      6853888.00
      1644404.98      6854287.98
#Sta/Elev= 30
  4750.6 1896.13  4753.1 1896.13  4760.8 1894.02  4781.2 1890.13  4811.8 1885.97
  4842.4 1880.98  4862.8 1876.23  4883.2 1872.21  4913.8 1868.99  4924.0 1868.38
  4934.2 1866.97  4964.8 1859.92  4969.8 1856.79  4970.3 1856.29  4979.5 1856.29
  4980.0 1856.79  4995.3 1859.08  5062.1 1861.71  5090.4 1861.48  5161.1 1863.89
  5231.8 1864.79  5246.0 1864.38  5288.4 1864.71  5345.0 1865.64  5472.2 1868.98
  5486.4 1869.56  5528.8 1872.73  5557.1 1875.87  5567.7 1877.57  5571.2 1877.57
#Mann=3,-1,0
  4750.6    0.05       0  4969.8    0.05       0  4980.0    0.05       0
Bank Sta=4969.8,4980
Exp/Cntr=0.3,0.1

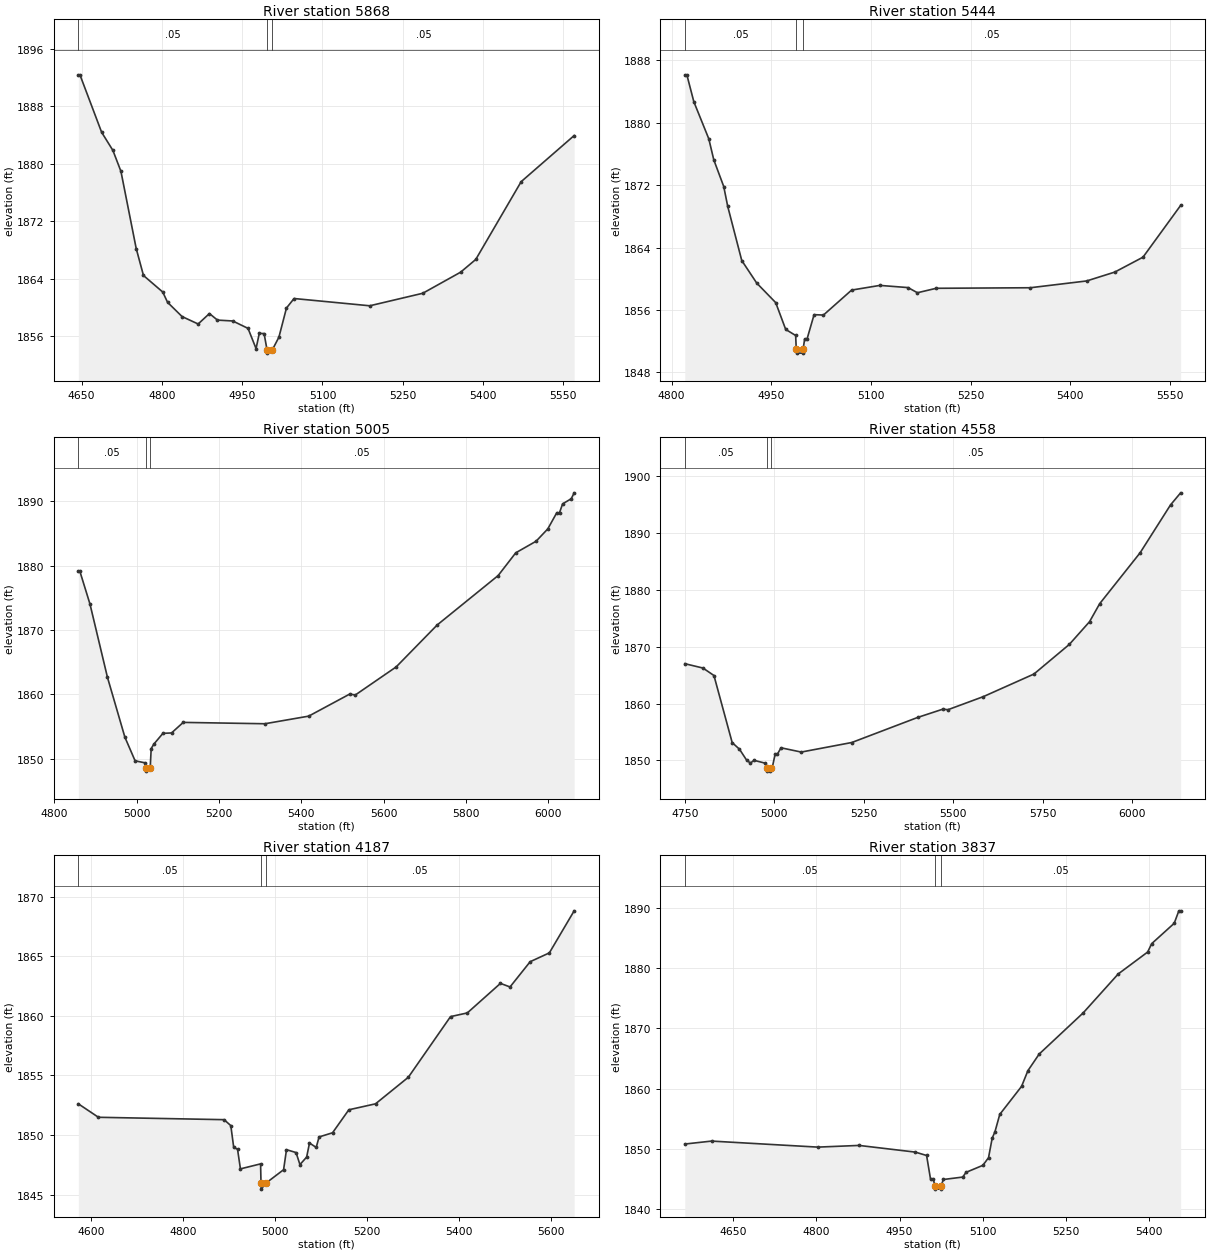
Type RM Length L Ch R = 1,5868,424,424,424
BEGIN DESCRIPTION:
Deadman 66 7.0
END DESCRIPTION:
XS GIS Cut Line= 3
      1643505.01      6853888.02      1643705.00      6854188.00
      1644104.99      6854587.99
#Sta/Elev= 30
  4644.0 1892.35  4647.0 1892.35  4687.5 1884.37  4708.6 1881.84  4723.6 1878.93
  4752.1 1868.21  4765.7 1864.46  4801.7 1862.16  4810.7 1860.73  4837.8 1858.75
  4867.8 1857.72  4888.9 1859.17  4903.9 1858.26  4932.4 1858.14  4961.0 1857.11
  4976.0 1854.30  4982.0 1856.41  4991.0 1856.39  4996.4 1854.17  4996.9 1853.67
  5006.7 1854.17  5018.7 1855.89  5032.8 1859.94  5047.0 1861.26  5188.4 1860.25
  5287.4 1861.99  5358.1 1864.92  5386.4 1866.69  5471.2 1877.50  5570.2 1883.91
#Mann=3,-1,0
  4644.0    0.05       0  4996.4    0.05       0  5006.7    0.05       0
Bank Sta=4996.4,5006.7
Exp/Cntr=0.3,0.1

Type RM Length L Ch R = 1,5444,439,439,439
BEGIN DESCRIPTION:
Deadman 66 6.0
END DESCRIPTION:
XS GIS Cut Line= 3
      1643204.96      6854187.97      1643355.00      6854288.00
      1643754.99      6854687.99
#Sta/Elev= 30
  4820.0 1886.15  4823.1 1886.15  4833.6 1882.70  4856.1 1877.95  4863.6 1875.26
  4878.6 1871.83  4884.6 1869.28  4905.7 1862.35  4928.2 1859.46  4956.8 1856.95
  4971.8 1853.52  4986.8 1852.74  4987.7 1850.98  4988.2 1850.48  4997.5 1850.48
  4998.0 1850.98  5000.3 1852.28  5003.9 1852.28  5014.5 1855.41  5028.6 1855.36
  5071.0 1858.56  5113.5 1859.16  5155.9 1858.88  5170.0 1858.22  5198.3 1858.79
  5339.7 1858.86  5424.6 1859.73  5467.0 1860.87  5509.4 1862.78  5566.0 1869.41
#Mann=3,-1,0
  4820.0    0.05       0  4987.7    0.05       0  4998.0    0.05       0
Bank Sta=4987.7,4998
Exp/Cntr=0.3,0.1

Type RM Length L Ch R = 1,5005,447,447,447
BEGIN DESCRIPTION:
Deadman 66 5.0
END DESCRIPTION:
XS GIS Cut Line= 3
      1642955.01      6854488.01      1643055.00      6854588.00
      1643854.98      6855287.98
#Sta/Elev= 30
  4858.6 1879.15  4862.1 1879.15  4886.9 1874.01  4929.3 1862.64  4971.7 1853.33
  4996.5 1849.66  5021.4 1849.34  5022.9 1848.56  5023.4 1848.06  5033.2 1848.56
  5035.6 1851.57  5042.2 1852.27  5064.1 1853.93  5085.0 1853.99  5113.4 1855.63
  5311.8 1855.42  5418.1 1856.60  5517.8 1860.03  5531.5 1859.89  5630.7 1864.25
  5730.4 1870.77  5878.4 1878.44  5921.1 1881.97  5970.5 1883.77  5999.0 1885.69
  6020.8 1888.20  6027.4 1888.20  6035.0 1889.58  6055.9 1890.37  6063.0 1891.29
#Mann=3,-1,0
  4858.6    0.05       0  5022.9    0.05       0  5033.2    0.05       0
Bank Sta=5022.9,5033.2
Exp/Cntr=0.3,0.1

Type RM Length L Ch R = 1,4558,371,371,371
BEGIN DESCRIPTION:
Deadman 66 4.0
END DESCRIPTION:
XS GIS Cut Line= 3
      1642755.01      6854688.04      1642805.00      6854938.00
      1643605.02      6855738.02
#Sta/Elev= 30
  4749.7 1867.01  4800.6 1866.24  4831.2 1864.93  4882.2 1853.14  4902.6 1851.98
  4923.0 1850.02  4933.2 1849.56  4943.4 1850.02  4974.0 1849.54  4979.0 1848.63
  4979.5 1848.13  4989.0 1848.13  4989.5 1848.63  4994.4 1848.80  5002.1 1851.06
  5008.1 1851.06  5018.7 1852.23  5075.3 1851.48  5216.7 1853.16  5400.6 1857.56
  5471.3 1859.02  5485.4 1858.92  5584.4 1861.22  5725.9 1865.19  5824.9 1870.40
  5881.4 1874.39  5909.7 1877.55  6022.8 1886.50  6107.7 1894.90  6136.0 1897.03
#Mann=3,-1,0
  4749.7    0.05       0  4979.0    0.05       0  4989.5    0.05       0
Bank Sta=4979,4989.5
Exp/Cntr=0.3,0.1

Type RM Length L Ch R = 1,4187,350,350,350
BEGIN DESCRIPTION:
Mapping XS 5f71a76a
END DESCRIPTION:
XS GIS Cut Line= 4
      1642667.03      6854830.04      1642593.25      6854986.28
      1642549.84      6855051.39      1643043.70      6855714.19
#Sta/Elev= 30
  4572.3 1852.62  4616.0 1851.49  4889.1 1851.29  4903.7 1850.79  4910.0 1848.96
  4918.3 1848.81  4924.6 1847.16  4968.4 1847.58  4969.3 1845.96  4969.8 1845.46
  4979.9 1845.96  5018.4 1847.09  5024.7 1848.77  5045.5 1848.53  5053.9 1847.52
  5068.5 1848.15  5074.7 1849.33  5089.3 1848.96  5095.5 1849.84  5124.8 1850.19
  5160.2 1852.12  5218.2 1852.62  5289.5 1854.85  5381.2 1859.94  5417.7 1860.25
  5489.7 1862.73  5510.5 1862.43  5554.3 1864.55  5596.0 1865.29  5649.9 1868.82
#Mann=3,-1,0
  4572.3    0.05       0  4969.3    0.03       0  4979.9    0.05       0
Bank Sta=4969.3,4979.9
Exp/Cntr=0.3,0.1

Type RM Length L Ch R = 1,3837,226,226,226
BEGIN DESCRIPTION:
Mapping XS 43af4845
END DESCRIPTION:
XS GIS Cut Line= 3
      1642572.31      6854881.86      1642449.83      6855134.49
      1642338.81      6855739.33
#Sta/Elev= 30
  4562.1 1850.83  4610.5 1851.32  4802.3 1850.32  4876.9 1850.60  4978.6 1849.49
  4998.9 1848.93  5006.0 1845.02  5011.1 1845.00  5014.0 1843.85  5014.5 1843.35
  5024.1 1843.35  5024.6 1843.85  5029.4 1844.95  5064.2 1845.35  5070.1 1846.13
  5100.6 1847.30  5110.8 1848.57  5117.4 1851.81  5122.4 1852.87  5131.1 1855.75
  5170.5 1860.40  5181.9 1863.00  5202.3 1865.76  5281.8 1872.59  5345.1 1879.05
  5398.2 1882.68  5405.6 1884.08  5446.2 1887.45  5454.6 1889.52  5457.8 1889.52
#Mann=3,-1,0
  4562.1    0.05       0  5014.0    0.05       0  5024.6    0.05       0
Bank Sta=5014,5024.6
Exp/Cntr=0.3,0.1

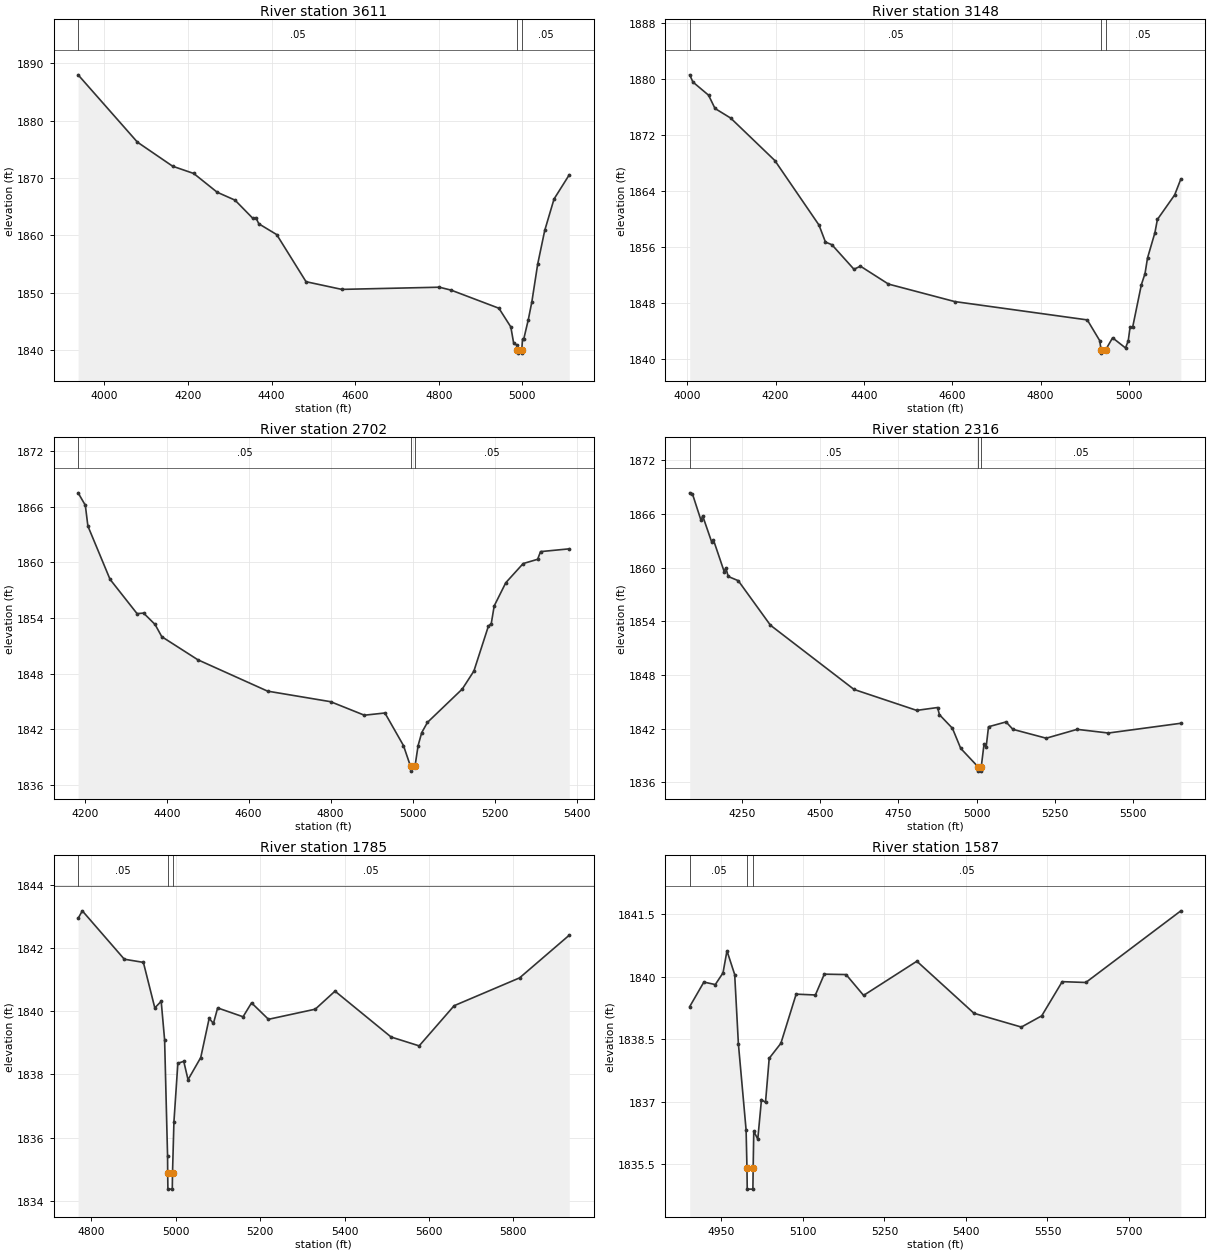
Type RM Length L Ch R = 1,3611,463,463,463
BEGIN DESCRIPTION:
Deadman 66 3.0
END DESCRIPTION:
XS GIS Cut Line= 3
      1642954.97      6854388.04      1642255.00      6855188.00
      1642154.97      6855238.01
#Sta/Elev= 30
  3937.3 1888.00  4079.1 1876.26  4163.6 1872.05  4213.9 1870.79  4269.9 1867.52
  4312.6 1866.14  4355.3 1862.96  4362.5 1863.08  4369.6 1862.01  4412.3 1860.13
  4482.5 1851.91  4567.9 1850.57  4801.4 1850.95  4829.9 1850.43  4943.8 1847.28
  4972.3 1844.02  4978.9 1841.28  4986.5 1840.85  4987.8 1839.95  4988.3 1839.45
  4997.9 1839.45  4998.4 1839.95  5000.3 1841.87  5003.1 1841.87  5014.2 1845.31
  5022.6 1848.39  5036.6 1854.99  5053.4 1860.85  5075.7 1866.34  5112.1 1870.56
#Mann=3,-1,0
  3937.3    0.05       0  4987.8    0.05       0  4998.4    0.05       0
Bank Sta=4987.8,4998.4
Exp/Cntr=0.3,0.1

Type RM Length L Ch R = 1,3148,446,446,446
BEGIN DESCRIPTION:
Deadman 66 2.0
END DESCRIPTION:
XS GIS Cut Line= 3
      1642805.00      6854238.00      1642005.00      6854838.00
      1641955.00      6854937.99
#Sta/Elev= 30
  4005.6 1880.61  4012.9 1879.58  4048.3 1877.70  4062.9 1875.80  4098.3 1874.43
  4198.3 1868.36  4298.3 1859.13  4312.9 1856.70  4327.5 1856.32  4377.5 1852.81
  4392.1 1853.25  4455.6 1850.69  4605.6 1848.19  4905.6 1845.57  4933.7 1842.61
  4936.7 1841.32  4937.2 1840.82  4947.4 1841.32  4962.9 1843.01  4992.1 1841.56
  4998.3 1842.57  5002.5 1844.56  5008.4 1844.56  5028.0 1850.60  5036.3 1852.20
  5041.9 1854.41  5058.7 1858.05  5064.3 1859.93  5103.4 1863.44  5117.4 1865.72
#Mann=3,-1,0
  4005.6    0.05       0  4936.7    0.05       0  4947.4    0.05       0
Bank Sta=4936.7,4947.4
Exp/Cntr=0.3,0.1

Type RM Length L Ch R = 1,2702,386,386,386
BEGIN DESCRIPTION:
Mapping XS f8f0697e
END DESCRIPTION:
XS GIS Cut Line= 3
      1642576.14      6854055.02      1641841.19      6854445.46
      1641582.27      6854704.38
#Sta/Elev= 30
  4183.8 1867.52  4201.4 1866.18  4207.7 1863.93  4261.7 1858.18  4327.7 1854.47
  4343.6 1854.53  4371.6 1853.30  4388.0 1851.98  4475.9 1849.49  4646.1 1846.10
  4799.9 1844.96  4882.2 1843.50  4932.4 1843.74  4977.7 1840.22  4995.0 1837.96
  4995.5 1837.46  5005.7 1837.96  5013.4 1840.22  5022.2 1841.62  5036.3 1842.73
  5121.2 1846.33  5149.5 1848.27  5184.8 1853.11  5191.9 1853.40  5199.0 1855.30
  5227.3 1857.81  5269.7 1859.88  5305.0 1860.34  5312.1 1861.17  5382.2 1861.47
#Mann=3,-1,0
  4183.8    0.05       0  4995.0    0.05       0  5005.7    0.05       0
Bank Sta=4995,5005.7
Exp/Cntr=0.3,0.1

Type RM Length L Ch R = 1,2316,531,531,531
BEGIN DESCRIPTION:
Mapping XS 59b77548
END DESCRIPTION:
XS GIS Cut Line= 3
      1642633.58      6853832.99      1641772.28      6854070.32
      1641263.96      6854513.68
#Sta/Elev= 30
  4083.5 1868.38  4092.4 1868.25  4119.8 1865.29  4124.9 1865.81  4154.1 1862.84
  4159.3 1863.12  4193.7 1859.56  4198.9 1859.99  4206.5 1859.03  4238.5 1858.56
  4341.3 1853.58  4608.2 1846.40  4808.1 1844.06  4874.8 1844.38  4880.7 1843.58
  4922.2 1842.06  4948.7 1839.81  5003.5 1837.77  5004.0 1837.27  5013.8 1837.27
  5014.3 1837.77  5023.2 1840.32  5029.8 1839.94  5037.4 1842.23  5093.4 1842.77
  5115.3 1841.94  5221.6 1840.95  5320.3 1841.94  5420.0 1841.53  5651.4 1842.62
#Mann=3,-1,0
  4083.5    0.05       0  5003.5    0.05       0  5014.3    0.05       0
Bank Sta=5003.5,5014.3
Exp/Cntr=0.3,0.1

Type RM Length L Ch R = 1,1785,198,198,198
BEGIN DESCRIPTION:
Mapping XS 38571e9b
END DESCRIPTION:
XS GIS Cut Line= 4
      1641676.58      6853446.39      1641546.44      6853645.42
      1641516.94      6854000.83      1641255.50      6854506.73
#Sta/Elev= 30
  4768.6 1842.93  4778.6 1843.17  4878.1 1841.64  4923.3 1841.54  4950.4 1840.10
  4965.5 1840.31  4973.6 1839.09  4980.6 1835.42  4980.9 1834.87  4981.4 1834.37
  4991.8 1834.37  4992.3 1834.87  4995.7 1836.50  5005.0 1838.35  5019.0 1838.41
  5029.1 1837.83  5059.2 1838.53  5079.2 1839.77  5089.3 1839.61  5099.3 1840.10
  5159.5 1839.82  5179.6 1840.26  5219.7 1839.74  5330.6 1840.06  5377.4 1840.63
  5510.3 1839.18  5576.8 1838.90  5659.7 1840.17  5814.8 1841.05  5932.5 1842.40
#Mann=3,-1,0
  4768.6    0.05       0  4980.9    0.05       0  4992.3    0.05       0
Bank Sta=4980.9,4992.3
Exp/Cntr=0.3,0.1

Type RM Length L Ch R = 1,1587,515,515,515
BEGIN DESCRIPTION:
Mapping XS 6d0479b4
END DESCRIPTION:
XS GIS Cut Line= 4
      1641331.76      6853674.41      1641494.97      6853850.18
      1641482.42      6854044.76      1641254.15      6854454.41
#Sta/Elev= 30
  4891.6 1839.28  4917.7 1839.87  4938.7 1839.81  4952.9 1840.09  4960.2 1840.62
  4974.4 1840.05  4981.2 1838.39  4995.4 1836.32  4997.0 1835.40  4997.5 1834.90
  5007.9 1834.90  5008.4 1835.40  5009.5 1836.29  5016.9 1836.10  5023.7 1837.05
  5031.1 1836.98  5037.9 1838.04  5059.4 1838.40  5087.5 1839.58  5122.9 1839.56
  5139.3 1840.06  5179.4 1840.05  5211.6 1839.55  5309.6 1840.37  5414.8 1839.12
  5501.9 1838.79  5539.4 1839.06  5577.1 1839.88  5620.5 1839.86  5795.4 1841.58
#Mann=3,-1,0
  4891.6    0.05       0  4997.0    0.05       0  5008.4    0.05       0
Bank Sta=4997,5008.4
Exp/Cntr=0.3,0.1

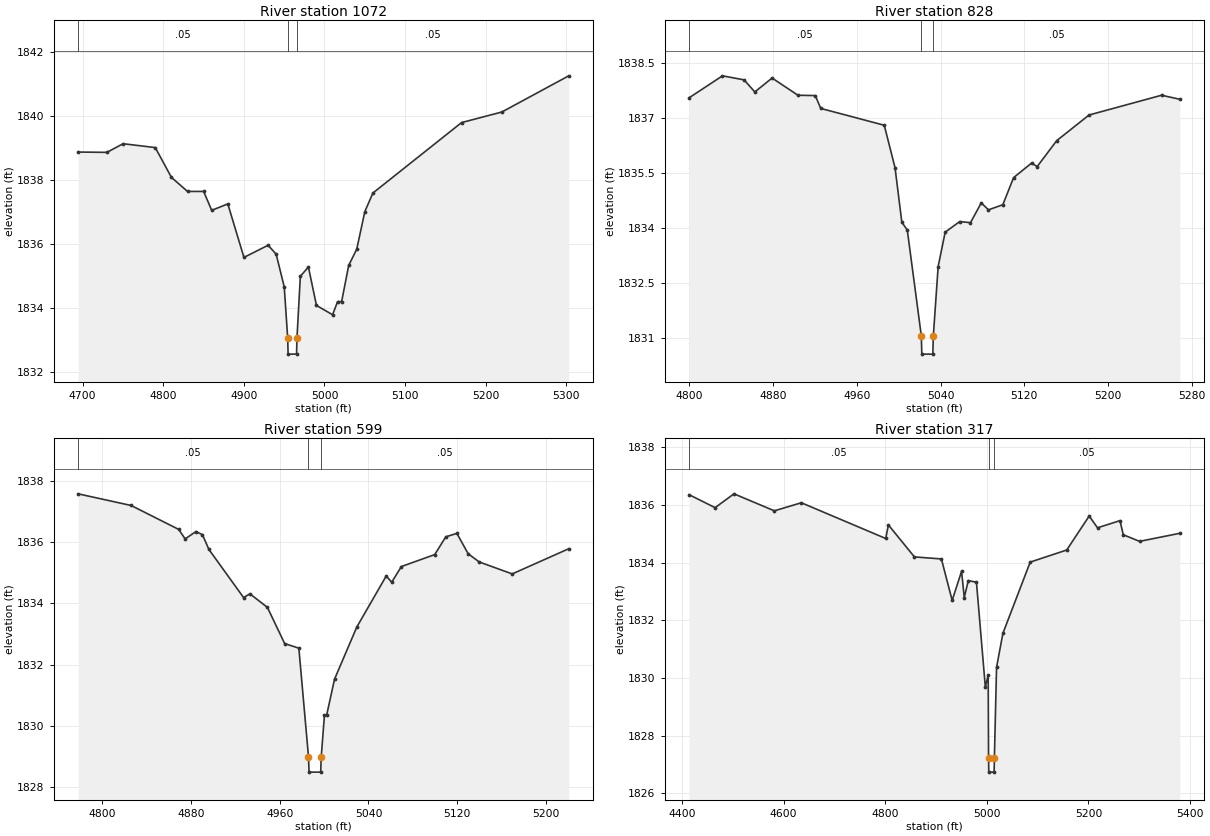
Type RM Length L Ch R = 1,1072,244,244,244
BEGIN DESCRIPTION:
Mapping XS 21da1baf
END DESCRIPTION:
XS GIS Cut Line= 3
      1641196.83      6853872.18      1641196.83      6854195.40
      1641193.69      6854480.96
#Sta/Elev= 30
  4694.3 1838.87  4730.1 1838.86  4750.1 1839.13  4790.1 1839.01  4810.1 1838.08
  4830.1 1837.64  4850.1 1837.64  4860.1 1837.05  4880.1 1837.25  4900.1 1835.58
  4930.1 1835.96  4940.1 1835.68  4950.1 1834.66  4954.4 1833.06  4954.9 1832.56
  4965.4 1832.56  4965.9 1833.06  4970.1 1834.99  4980.1 1835.28  4990.1 1834.08
  5010.1 1833.79  5016.3 1834.20  5021.3 1834.20  5030.1 1835.33  5040.1 1835.84
  5050.1 1837.01  5060.1 1837.59  5170.1 1839.79  5220.1 1840.12  5303.1 1841.25
#Mann=3,-1,0
  4694.3    0.05       0  4954.4    0.05       0  4965.9    0.05       0
Bank Sta=4954.4,4965.9
Exp/Cntr=0.3,0.1

Type RM Length L Ch R = 1,828,229,229,229
BEGIN DESCRIPTION:
Mapping XS 835ad427
END DESCRIPTION:
XS GIS Cut Line= 2
      1641049.33      6853847.02      1640936.35      6854302.10
#Sta/Elev= 30
  4799.7 1837.55  4831.6 1838.15  4852.2 1838.04  4862.5 1837.71  4879.0 1838.09
  4903.7 1837.62  4920.3 1837.61  4925.5 1837.26  4986.2 1836.80  4996.5 1835.64
  5003.0 1834.15  5008.2 1833.94  5021.6 1831.05  5022.1 1830.55  5032.6 1830.55
  5033.1 1831.05  5037.7 1832.94  5044.4 1833.88  5058.3 1834.17  5068.6 1834.14
  5078.9 1834.68  5085.8 1834.49  5099.5 1834.63  5109.8 1835.37  5127.1 1835.77
  5132.3 1835.67  5151.0 1836.38  5181.9 1837.08  5251.2 1837.62  5268.6 1837.51
#Mann=3,-1,0
  4799.7    0.05       0  5021.6    0.05       0  5033.1    0.05       0
Bank Sta=5021.6,5033.1
Exp/Cntr=0.3,0.1

Type RM Length L Ch R = 1,599,282,282,282
BEGIN DESCRIPTION:
Mapping XS b84b32ef
END DESCRIPTION:
XS GIS Cut Line= 3
      1640986.53      6853865.89      1640795.12      6853978.86
      1640813.95      6854198.49
#Sta/Elev= 30
  4778.0 1837.57  4825.9 1837.19  4868.8 1836.41  4874.6 1836.10  4884.3 1836.34
  4890.2 1836.24  4896.0 1835.76  4927.3 1834.19  4933.1 1834.31  4948.8 1833.87
  4964.4 1832.69  4977.2 1832.54  4985.9 1829.00  4986.4 1828.50  4996.9 1828.50
  4997.4 1829.00  5000.3 1830.36  5002.3 1830.36  5009.4 1831.53  5029.5 1833.23
  5056.0 1834.89  5061.0 1834.69  5069.7 1835.20  5099.8 1835.59  5109.8 1836.17
  5119.8 1836.28  5129.9 1835.62  5139.9 1835.35  5169.7 1834.96  5220.7 1835.78
#Mann=3,-1,0
  4778.0    0.05       0  4985.9    0.05       0  4997.4    0.05       0
Bank Sta=4985.9,4997.4
Exp/Cntr=0.3,0.1

Type RM Length L Ch R = 1,317,0,0,0
BEGIN DESCRIPTION:
Deadman 66 1.0
END DESCRIPTION:
XS GIS Cut Line= 3
      1641093.27      6853633.64      1640559.74      6853821.94
      1640744.89      6854176.54
#Sta/Elev= 30
  4414.0 1836.36  4465.2 1835.91  4502.3 1836.39  4581.8 1835.80  4634.9 1836.08
  4801.0 1834.84  4806.3 1835.31  4857.5 1834.20  4910.6 1834.13  4931.8 1832.69
  4950.3 1833.70  4955.6 1832.79  4963.6 1833.38  4979.6 1833.32  4997.1 1829.68
  5002.7 1830.10  5003.4 1827.23  5003.9 1826.73  5014.4 1826.73  5014.9 1827.23
  5019.2 1830.37  5031.7 1831.55  5085.4 1834.02  5157.3 1834.44  5201.5 1835.62
  5217.9 1835.21  5262.1 1835.46  5268.6 1834.97  5300.6 1834.74  5379.8 1835.02
#Mann=3,-1,0
  4414.0    0.05       0  5003.4    0.05       0  5014.9    0.05       0
Bank Sta=5003.4,5014.9
Exp/Cntr=0.3,0.1

Chan Stop Cuts=-1