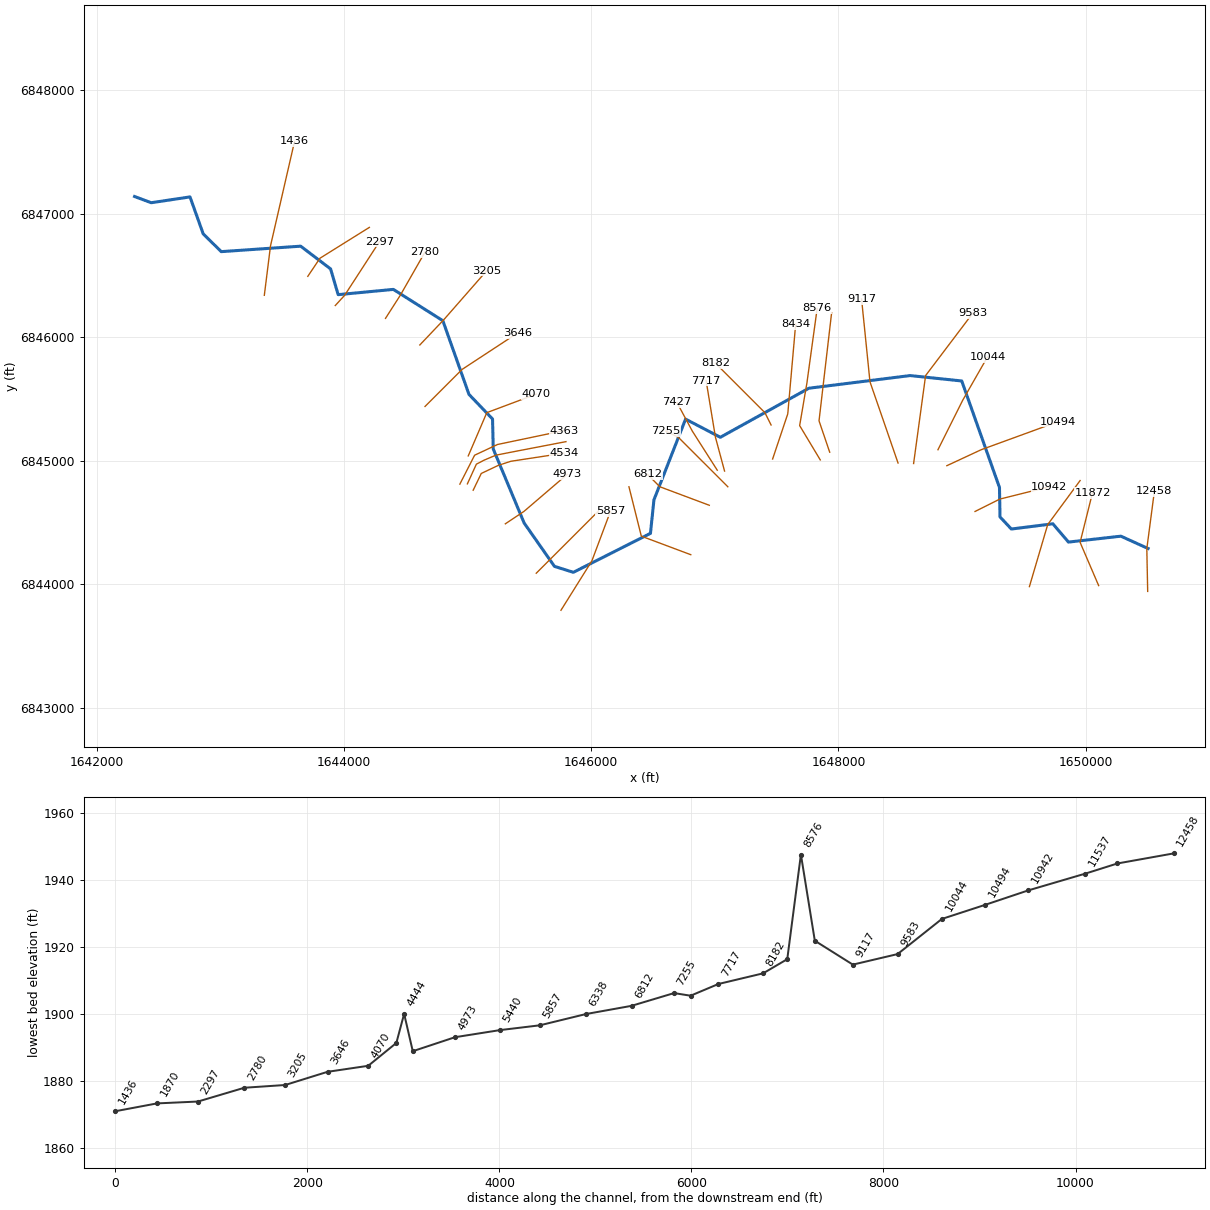
--- Deadman 67.prj (project) ---

Proj Title=Deadman 67 Base Level Engineering
Current Plan=p01
Default Exp/Contr=0.3,0.1
English Units
Geom File=g01
Flow File=f01
Plan File=p01
BEGIN DESCRIPTION:
Deadman 67
END DESCRIPTION:

--- Deadman 67.p01 (plan) ---

Plan Title=Multiple Run
Short Identifier=Multiple
Geom File=g01
Flow File=f01
Subcritical Flow
K Sum by GR= 0
Std Step Tol= 0.01
Critical Tol= 0.01
Num of Std Step Trials= 20
Max Error Tol= 0.3
Flow Tol Ratio= 0.001
Split Flow NTrial= 30
Split Flow Tol= 0.02
Split Flow Ratio= 0.02
Log Output Level= 0
Friction Slope Method= 1
Unsteady Friction Slope Method= 2
Unsteady Bridges Friction Slope Method= 1
Parabolic Critical Depth
Global Vel Dist=  1 , 1 , 1
Global Log Level= 0
CheckData=True
Encroach Param= -1, 0, 0, 0
BEGIN DESCRIPTION:
Multiple Run
END DESCRIPTION:

--- Deadman 67.f01 (steady flow) ---

Flow Title=Multiple
Number of Profiles=7
Profile Names=10-year,25-year,50-year,1pct_min,100-year,1pct_plu,500-year
River Rch & RM= Deadman 67,Reach-1,12458
     219     299     364     221     441     879     654
River Rch & RM= Deadman 67,Reach-1,11872
     331     464     576     356     710    1416    1093
River Rch & RM= Deadman 67,Reach-1,5857
     577     833    1055     663    1323    2640    2111
Boundary for River Rch & Prof#=Deadman 67,Reach-1,1
Up Type=0
Dn Type=3
Dn Slope=0.005
Boundary for River Rch & Prof#=Deadman 67,Reach-1,2
Up Type=0
Dn Type=3
Dn Slope=0.005
Boundary for River Rch & Prof#=Deadman 67,Reach-1,3
Up Type=0
Dn Type=3
Dn Slope=0.005
Boundary for River Rch & Prof#=Deadman 67,Reach-1,4
Up Type=0
Dn Type=3
Dn Slope=0.005
Boundary for River Rch & Prof#=Deadman 67,Reach-1,5
Up Type=0
Dn Type=3
Dn Slope=0.005
Boundary for River Rch & Prof#=Deadman 67,Reach-1,6
Up Type=0
Dn Type=3
Dn Slope=0.005
Boundary for River Rch & Prof#=Deadman 67,Reach-1,7
Up Type=0
Dn Type=3
Dn Slope=0.005

--- Deadman 67.g01 (geometry) ---

Geom Title=Existing Conditions

River Reach=Deadman 67,Reach-1
Reach XY= 30
      1650505.00      6844288.00      1650284.97      6844387.94
      1649860.85      6844340.04      1649734.74      6844488.12
      1649398.79      6844445.80      1649307.05      6844543.84
      1649302.74      6844782.06      1648997.32      6845644.52
      1648579.92      6845688.20      1647760.94      6845585.74
      1647044.36      6845188.56      1646763.15      6845335.51
      1646507.24      6844682.07      1646478.97      6844410.81
      1645855.04      6844095.31      1645702.56      6844143.51
      1645457.33      6844493.97      1645207.07      6845093.86
      1645201.46      6845336.54      1645010.83      6845535.70
      1644799.41      6846132.39      1644399.07      6846385.76
      1643952.32      6846343.30      1643891.36      6846551.34
      1643649.07      6846735.76      1643006.46      6846691.54
      1642860.52      6846835.57      1642753.77      6847134.57
      1642439.83      6847087.52      1642305.00      6847138.00

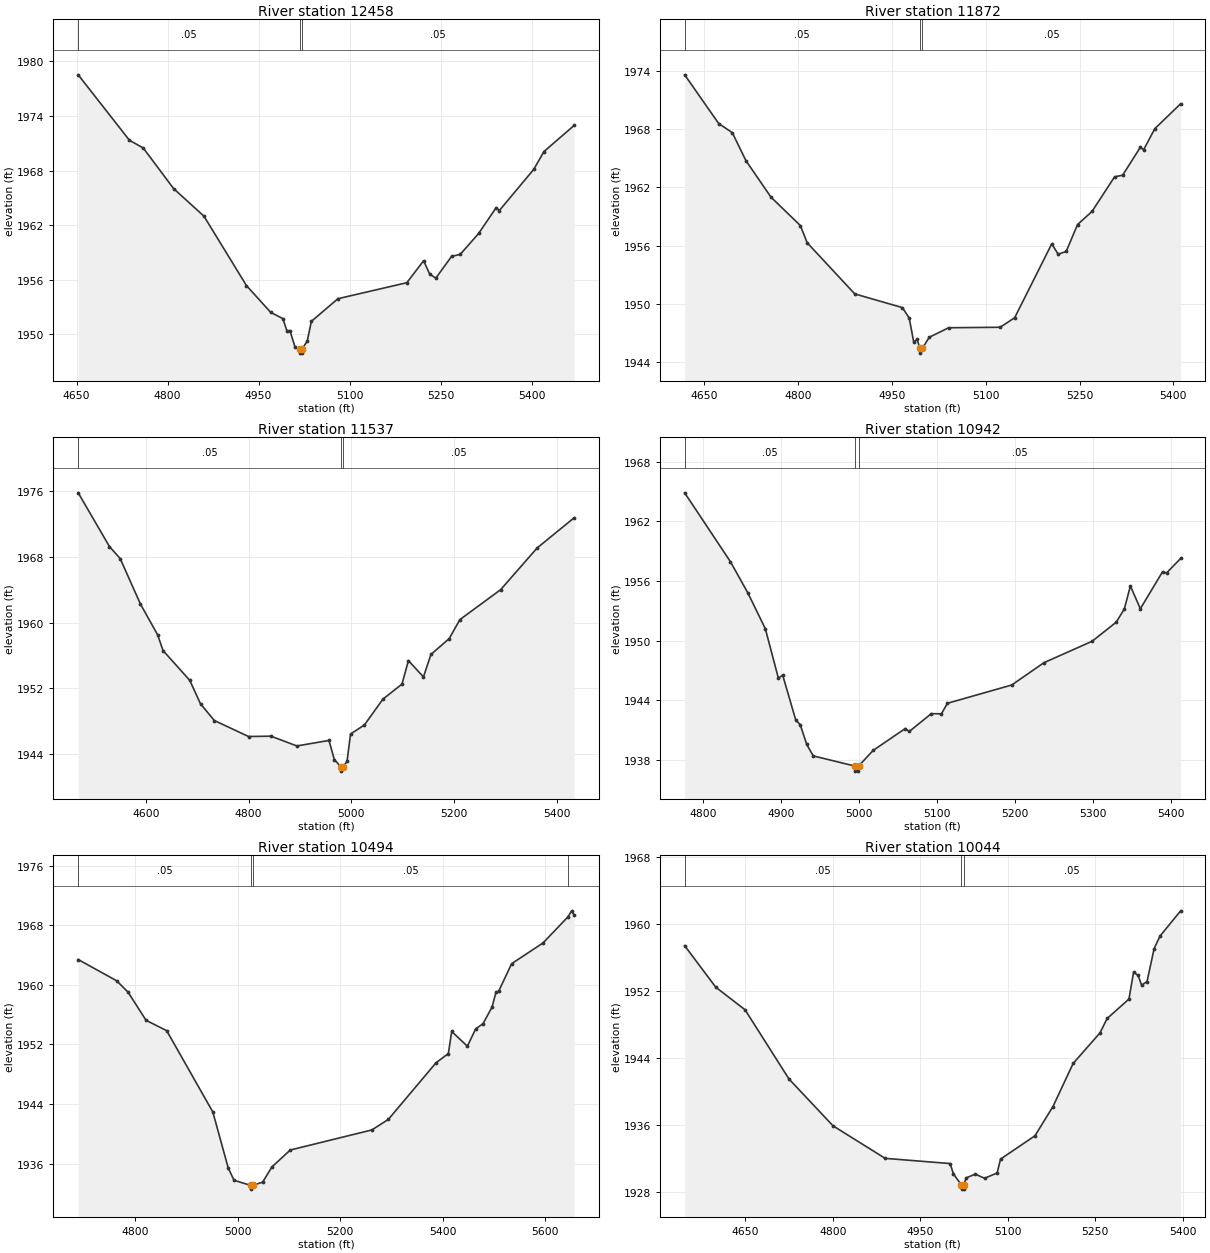
Type RM Length L Ch R = 1,12458,586,586,586
BEGIN DESCRIPTION:
Deadman 67 26.0
END DESCRIPTION:
XS GIS Cut Line= 3
      1650501.77      6843940.82      1650494.72      6844286.19
      1650556.28      6844754.01
#Sta/Elev= 30
  4652.7 1978.53  4737.1 1971.34  4759.9 1970.49  4809.9 1966.03  4859.9 1963.00
  4929.9 1955.38  4969.9 1952.43  4990.0 1951.74  4996.5 1950.42  5001.6 1950.42
  5010.1 1948.60  5018.1 1948.45  5018.4 1947.95  5021.9 1947.95  5022.1 1948.45
  5030.2 1949.28  5036.9 1951.44  5080.7 1953.93  5194.3 1955.69  5221.9 1958.10
  5232.0 1956.63  5242.0 1956.19  5267.9 1958.57  5282.4 1958.81  5312.6 1961.10
  5341.5 1963.94  5346.6 1963.61  5403.4 1968.14  5420.2 1970.10  5470.0 1972.97
#Mann=3,-1,0
  4652.7    0.05       0  5018.1    0.05       0  5022.1    0.05       0
Bank Sta=5018.1,5022.1
Exp/Cntr=0.3,0.1

Type RM Length L Ch R = 1,11872,335,335,335
BEGIN DESCRIPTION:
Deadman 67 25.0
END DESCRIPTION:
XS GIS Cut Line= 3
      1650105.02      6843987.96      1649955.00      6844338.00
      1650054.99      6844737.96
#Sta/Elev= 30
  4618.6 1973.56  4673.0 1968.55  4694.8 1967.61  4716.6 1964.73  4756.5 1960.99
  4803.6 1958.06  4814.5 1956.29  4890.6 1951.03  4966.8 1949.62  4977.7 1948.54
  4984.9 1946.08  4990.4 1946.35  4994.7 1945.44  4994.9 1944.94  4998.8 1945.44
  5009.7 1946.57  5040.7 1947.55  5123.1 1947.60  5146.3 1948.58  5205.6 1956.18
  5215.9 1955.11  5228.8 1955.40  5246.8 1958.16  5270.0 1959.51  5306.1 1963.07
  5319.0 1963.24  5347.3 1966.11  5352.5 1965.85  5370.5 1968.03  5411.7 1970.58
#Mann=3,-1,0
  4618.6    0.05       0  4994.7    0.05       0  4998.8    0.05       0
Bank Sta=4994.7,4998.8
Exp/Cntr=0.3,0.1

Type RM Length L Ch R = 1,11537,595,595,595
BEGIN DESCRIPTION:
Deadman 67 24.0
END DESCRIPTION:
XS GIS Cut Line= 3
      1649544.83      6843979.54      1649692.86      6844481.81
      1649955.01      6844838.02
#Sta/Elev= 30
  4468.0 1975.82  4528.9 1969.27  4549.8 1967.80  4589.3 1962.25  4622.7 1958.51
  4633.2 1956.60  4685.3 1952.96  4706.2 1950.10  4733.1 1948.07  4799.7 1946.12
  4843.5 1946.16  4893.8 1944.97  4956.4 1945.64  4966.8 1943.31  4979.9 1942.40
  4980.2 1941.90  4984.0 1942.40  4991.6 1943.10  4998.4 1946.42  5025.4 1947.53
  5061.4 1950.67  5098.6 1952.51  5111.1 1955.37  5140.4 1953.38  5155.0 1956.12
  5190.5 1958.05  5211.4 1960.37  5290.8 1964.02  5361.8 1969.10  5433.9 1972.78
#Mann=3,-1,0
  4468.0    0.05       0  4979.9    0.05       0  4984.0    0.05       0
Bank Sta=4979.9,4984
Exp/Cntr=0.3,0.1

Type RM Length L Ch R = 1,10942,448,448,448
BEGIN DESCRIPTION:
Deadman 67 23.0
END DESCRIPTION:
XS GIS Cut Line= 3
      1649105.04      6844588.02      1649305.00      6844688.00
      1649705.03      6844788.01
#Sta/Elev= 30
  4776.4 1964.86  4835.1 1957.93  4857.4 1954.80  4879.8 1951.20  4896.5 1946.24
  4902.1 1946.52  4918.9 1942.00  4924.5 1941.56  4932.9 1939.56  4941.3 1938.41
  4995.1 1937.38  4995.4 1936.88  4999.0 1936.88  4999.3 1937.38  5018.0 1938.96
  5059.2 1941.16  5064.4 1940.87  5092.7 1942.66  5105.6 1942.64  5113.3 1943.70
  5195.8 1945.54  5237.0 1947.78  5298.9 1949.94  5329.8 1951.86  5340.1 1953.18
  5347.9 1955.49  5360.7 1953.21  5389.1 1956.92  5394.2 1956.80  5412.3 1958.26
#Mann=3,-1,0
  4776.4    0.05       0  4995.1    0.05       0  4999.3    0.05       0
Bank Sta=4995.1,4999.3
Exp/Cntr=0.3,0.1

Type RM Length L Ch R = 1,10494,450,450,450
BEGIN DESCRIPTION:
Deadman 67 22.0
END DESCRIPTION:
XS GIS Cut Line= 3
      1648877.06      6844958.57      1649155.00      6845088.00
      1649775.46      6845314.46
#Sta/Elev= 30
  4689.2 1963.40  4764.1 1960.55  4786.2 1959.04  4821.5 1955.24  4861.7 1953.85
  4951.7 1942.93  4981.6 1935.44  4993.0 1933.76  5025.6 1933.07  5025.9 1932.57
  5029.8 1933.07  5049.0 1933.52  5066.9 1935.55  5102.7 1937.82  5261.9 1940.52
  5293.9 1941.93  5387.0 1949.54  5411.0 1950.77  5417.5 1953.74  5448.1 1951.76
  5464.2 1954.08  5478.6 1954.79  5496.1 1957.00  5503.8 1958.99  5509.2 1959.16
  5534.4 1962.84  5595.5 1965.62  5644.2 1969.13  5651.3 1969.94  5656.3 1969.37
#Mann=4,-1,0
  4689.2    0.05       0  5025.6    0.05       0  5029.8    0.05       0
  5644.2    0.12       0
Bank Sta=5025.6,5029.8
Exp/Cntr=0.3,0.1

Type RM Length L Ch R = 1,10044,461,461,461
BEGIN DESCRIPTION:
Deadman 67 21.0
END DESCRIPTION:
XS GIS Cut Line= 3
      1648804.98      6845087.96      1649005.00      6845488.00
      1649205.01      6845838.03
#Sta/Elev= 30
  4546.2 1957.39  4599.4 1952.45  4649.7 1949.75  4725.1 1941.49  4800.6 1935.91
  4890.0 1932.03  5001.4 1931.41  5007.1 1930.16  5020.8 1928.86  5021.1 1928.36
  5024.9 1928.36  5025.1 1928.86  5028.7 1929.70  5044.6 1930.15  5060.4 1929.65
  5082.0 1930.29  5087.8 1931.94  5146.8 1934.72  5177.7 1938.21  5212.3 1943.35
  5258.4 1947.00  5270.6 1948.71  5308.0 1951.03  5315.9 1954.22  5323.9 1953.84
  5329.6 1952.68  5339.0 1953.12  5351.2 1957.05  5361.3 1958.54  5396.6 1961.55
#Mann=3,-1,0
  4546.2    0.05       0  5020.8    0.05       0  5025.1    0.05       0
Bank Sta=5020.8,5025.1
Exp/Cntr=0.3,0.1

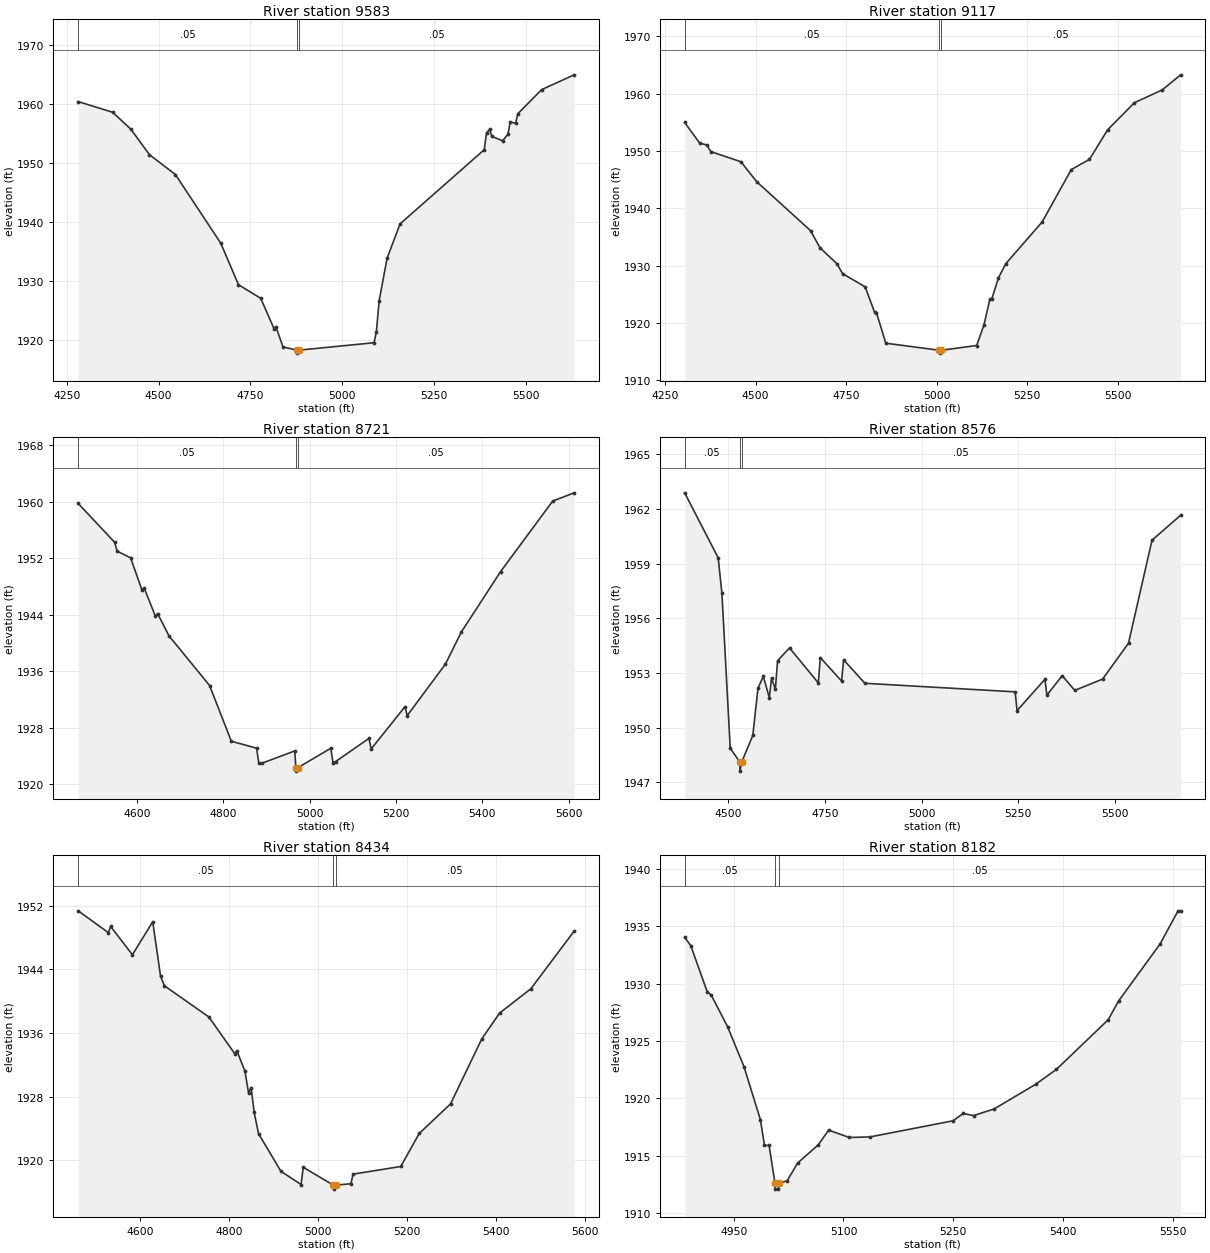
Type RM Length L Ch R = 1,9583,466,466,466
BEGIN DESCRIPTION:
Deadman 67 20.0
END DESCRIPTION:
XS GIS Cut Line= 3
      1648607.94      6844975.91      1648705.00      6845688.00
      1649085.39      6846191.23
#Sta/Elev= 30
  4281.3 1960.40  4375.0 1958.60  4424.7 1955.72  4475.2 1951.42  4545.8 1948.07
  4669.4 1936.43  4717.4 1929.43  4777.9 1927.13  4814.1 1922.00  4819.1 1922.35
  4838.5 1918.91  4876.7 1918.36  4877.0 1917.86  4881.1 1918.36  5086.3 1919.62
  5092.6 1921.47  5100.3 1926.74  5121.7 1933.88  5157.1 1939.72  5386.0 1952.26
  5392.3 1955.08  5400.6 1955.73  5406.8 1954.52  5435.9 1953.78  5450.5 1954.87
  5456.8 1956.95  5471.3 1956.74  5477.6 1958.35  5542.1 1962.42  5630.8 1964.93
#Mann=3,-1,0
  4281.3    0.05       0  4876.7    0.03       0  4881.1    0.05       0
Bank Sta=4876.7,4881.1
Exp/Cntr=0.3,0.1

Type RM Length L Ch R = 1,9117,396,396,396
BEGIN DESCRIPTION:
Deadman 67 19.0
END DESCRIPTION:
XS GIS Cut Line= 3
      1648482.07      6844980.27      1648255.00      6845638.00
      1648186.93      6846308.43
#Sta/Elev= 30
  4304.1 1954.97  4345.2 1951.39  4365.2 1951.03  4376.4 1949.88  4459.4 1948.11
  4502.7 1944.65  4651.8 1936.08  4677.7 1933.10  4724.9 1930.30  4740.1 1928.58
  4802.5 1926.28  4828.4 1921.88  4833.7 1921.79  4859.6 1916.44  5007.6 1915.21
  5007.9 1914.71  5012.4 1915.21  5110.5 1916.04  5130.6 1919.61  5147.0 1924.10
  5152.1 1924.11  5170.8 1927.86  5190.9 1930.32  5291.4 1937.60  5371.8 1946.74
  5422.1 1948.53  5472.3 1953.69  5546.1 1958.41  5623.1 1960.65  5673.8 1963.28
#Mann=3,-1,0
  4304.1    0.05       0  5007.6    0.03       0  5012.4    0.05       0
Bank Sta=5007.6,5012.4
Exp/Cntr=0.3,0.1

Type RM Length L Ch R = 1,8721,145,145,145
BEGIN DESCRIPTION:
Mapping XS fa4256c9
END DESCRIPTION:
XS GIS Cut Line= 3
      1647929.12      6845067.94      1647842.81      6845321.59
      1647944.74      6846197.45
#Sta/Elev= 30
  4463.4 1959.78  4548.0 1954.27  4553.5 1953.03  4584.9 1952.07  4611.0 1947.53
  4616.3 1947.81  4642.3 1943.81  4647.6 1944.17  4673.7 1941.03  4768.0 1933.98
  4818.3 1926.09  4876.9 1925.10  4881.9 1923.07  4888.8 1922.96  4965.4 1924.71
  4968.0 1922.35  4968.3 1921.85  4972.9 1922.35  5048.9 1925.09  5054.0 1923.06
  5059.9 1923.20  5137.5 1926.49  5142.5 1924.99  5221.0 1930.99  5226.1 1929.72
  5314.6 1937.01  5351.9 1941.60  5442.5 1950.12  5563.3 1960.12  5613.1 1961.29
#Mann=3,-1,0
  4463.4    0.05       0  4968.0    0.03       0  4972.9    0.05       0
Bank Sta=4968,4972.9
Exp/Cntr=0.3,0.1

Type RM Length L Ch R = 1,8576,142,142,142
BEGIN DESCRIPTION:
Mapping XS f095c165
END DESCRIPTION:
XS GIS Cut Line= 4
      1647852.73      6845005.44      1647686.06      6845283.21
      1647744.66      6845627.37      1647827.71      6846231.34
#Sta/Elev= 30
  4387.1 1962.88  4473.8 1959.31  4483.4 1957.37  4504.9 1948.87  4529.7 1948.11
  4530.1 1947.61  4534.6 1948.11  4563.3 1949.57  4576.7 1952.16  4590.5 1952.81
  4606.0 1951.64  4611.8 1952.73  4621.6 1952.09  4627.4 1953.67  4658.3 1954.37
  4732.8 1952.45  4737.9 1953.84  4793.0 1952.55  4798.1 1953.72  4853.2 1952.43
  5241.8 1951.96  5246.8 1950.93  5318.9 1952.65  5323.9 1951.78  5363.6 1952.85
  5396.0 1952.04  5468.0 1952.66  5535.0 1954.63  5595.8 1960.28  5669.8 1961.65
#Mann=3,-1,0
  4387.1    0.05       0  4529.7    0.03       0  4534.6    0.05       0
Bank Sta=4529.7,4534.6
Exp/Cntr=0.3,0.1

Type RM Length L Ch R = 1,8434,252,252,252
BEGIN DESCRIPTION:
Mapping XS a3b7db0f
END DESCRIPTION:
XS GIS Cut Line= 3
      1647467.33      6845012.42      1647589.88      6845378.22
      1647653.89      6846104.92
#Sta/Elev= 30
  4460.3 1951.38  4527.9 1948.64  4533.2 1949.41  4582.2 1945.85  4627.9 1950.01
  4645.5 1943.13  4654.2 1941.94  4754.1 1938.02  4812.0 1933.41  4817.2 1933.75
  4835.3 1931.18  4843.3 1928.47  4849.2 1929.13  4855.9 1926.02  4865.9 1923.32
  4916.1 1918.59  4961.4 1916.92  4966.4 1919.09  5034.1 1916.84  5034.5 1916.34
  5039.0 1916.84  5073.5 1917.02  5078.6 1918.23  5185.7 1919.19  5227.3 1923.36
  5297.6 1927.07  5367.9 1935.26  5408.0 1938.51  5478.3 1941.57  5575.6 1948.83
#Mann=3,-1,0
  4460.3    0.05       0  5034.1    0.05       0  5039.0    0.05       0
Bank Sta=5034.1,5039
Exp/Cntr=0.3,0.1

Type RM Length L Ch R = 1,8182,465,465,465
BEGIN DESCRIPTION:
Deadman 67 17.0
END DESCRIPTION:
XS GIS Cut Line= 3
      1647454.98      6845288.04      1647405.00      6845388.00
      1647005.03      6845787.97
#Sta/Elev= 30
  4883.1 1934.04  4891.4 1933.32  4913.8 1929.31  4919.4 1929.00  4941.8 1926.24
  4964.1 1922.77  4986.5 1918.16  4992.1 1915.91  4998.4 1915.91  5006.5 1912.60
  5006.9 1912.10  5011.1 1912.10  5011.5 1912.60  5023.1 1912.83  5037.3 1914.37
  5065.6 1915.96  5079.7 1917.24  5108.0 1916.60  5136.3 1916.65  5249.4 1918.05
  5263.6 1918.69  5277.7 1918.51  5306.0 1919.09  5362.6 1921.24  5390.8 1922.53
  5461.6 1926.86  5475.7 1928.49  5532.3 1933.45  5557.0 1936.35  5560.5 1936.35
#Mann=3,-1,0
  4883.1    0.05       0  5006.5    0.05       0  5011.5    0.05       0
Bank Sta=5006.5,5011.5
Exp/Cntr=0.3,0.1

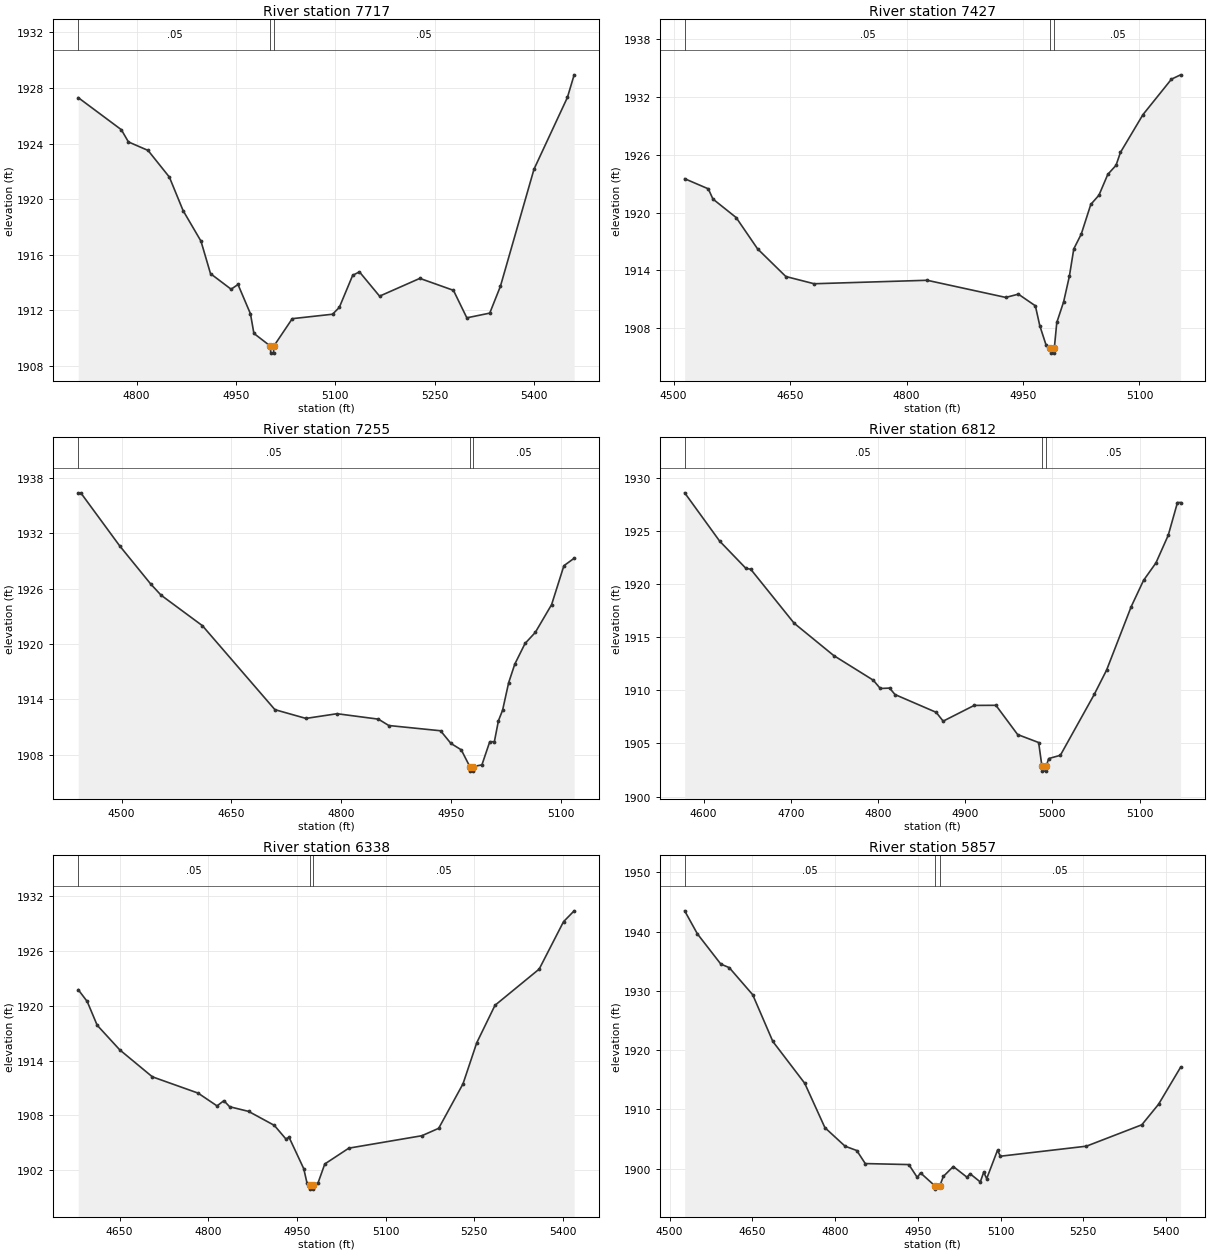
Type RM Length L Ch R = 1,7717,290,290,290
BEGIN DESCRIPTION:
Deadman 67 16.0
END DESCRIPTION:
XS GIS Cut Line= 3
      1647078.43      6844915.12      1647005.00      6845188.00
      1646929.12      6845647.79
#Sta/Elev= 30
  4712.0 1927.31  4777.1 1925.00  4787.8 1924.12  4817.4 1923.51  4849.6 1921.59
  4870.3 1919.18  4897.3 1916.98  4911.7 1914.64  4942.8 1913.52  4953.2 1913.86
  4972.0 1911.75  4977.2 1910.34  5002.2 1909.42  5002.6 1908.92  5006.8 1908.92
  5007.2 1909.42  5035.1 1911.40  5095.9 1911.72  5106.1 1912.21  5126.3 1914.52
  5136.5 1914.77  5166.9 1913.02  5227.7 1914.30  5278.4 1913.44  5298.6 1911.46
  5333.2 1911.80  5349.3 1913.73  5400.0 1922.16  5450.4 1927.32  5460.6 1928.95
#Mann=3,-1,0
  4712.0    0.05       0  5002.2    0.05       0  5007.2    0.05       0
Bank Sta=5002.2,5007.2
Exp/Cntr=0.3,0.1

Type RM Length L Ch R = 1,7427,172,172,172
BEGIN DESCRIPTION:
Mapping XS 6c88e739
END DESCRIPTION:
XS GIS Cut Line= 3
      1647019.40      6844922.09      1646818.01      6845238.07
      1646693.01      6845470.71
#Sta/Elev= 30
  4514.2 1923.52  4544.6 1922.47  4550.6 1921.41  4580.5 1919.49  4608.1 1916.24
  4644.5 1913.37  4680.9 1912.62  4826.5 1912.98  4927.8 1911.20  4944.0 1911.54
  4965.9 1910.33  4971.6 1908.27  4979.6 1906.28  4985.3 1905.92  4985.7 1905.42
  4990.0 1905.42  4990.3 1905.92  4993.5 1908.60  5002.3 1910.74  5009.7 1913.39
  5015.4 1916.24  5025.0 1917.77  5037.3 1920.85  5047.8 1921.81  5059.2 1923.97
  5069.8 1924.91  5075.5 1926.25  5104.5 1930.17  5141.2 1933.85  5153.0 1934.30
#Mann=3,-1,0
  4514.2    0.05       0  4985.3    0.05       0  4990.3    0.05       0
Bank Sta=4985.3,4990.3
Exp/Cntr=0.3,0.1

Type RM Length L Ch R = 1,7255,443,443,443
BEGIN DESCRIPTION:
Deadman 67 15.0
END DESCRIPTION:
XS GIS Cut Line= 3
      1647105.00      6844788.00      1646705.00      6845188.00
      1646604.99      6845238.00
#Sta/Elev= 30
  4440.8 1936.40  4444.3 1936.40  4497.4 1930.65  4539.8 1926.51  4553.9 1925.30
  4610.5 1921.98  4709.5 1912.87  4751.9 1911.92  4794.4 1912.43  4850.9 1911.84
  4865.1 1911.15  4935.8 1910.58  4949.9 1909.21  4964.1 1908.51  4975.7 1906.70
  4976.1 1906.20  4980.4 1906.20  4980.7 1906.70  4992.3 1906.88  5003.0 1909.39
  5009.3 1909.39  5014.9 1911.68  5020.5 1912.80  5028.8 1915.79  5037.2 1917.81
  5051.2 1920.05  5065.2 1921.25  5087.5 1924.27  5104.3 1928.49  5118.3 1929.30
#Mann=3,-1,0
  4440.8    0.05       0  4975.7    0.05       0  4980.7    0.05       0
Bank Sta=4975.7,4980.7
Exp/Cntr=0.3,0.1

Type RM Length L Ch R = 1,6812,474,474,474
BEGIN DESCRIPTION:
Deadman 67 14.0
END DESCRIPTION:
XS GIS Cut Line= 3
      1646955.04      6844637.99      1646555.00      6844788.00
      1646454.97      6844888.03
#Sta/Elev= 30
  4578.3 1928.56  4618.4 1924.02  4648.6 1921.45  4654.0 1921.38  4703.8 1916.30
  4749.2 1913.26  4794.6 1910.94  4802.6 1910.16  4813.3 1910.20  4819.5 1909.59
  4866.7 1907.92  4874.7 1907.09  4910.3 1908.57  4935.2 1908.58  4960.1 1905.83
  4984.2 1905.08  4987.9 1902.89  4988.3 1902.39  4992.6 1902.39  4993.0 1902.89
  4995.7 1903.57  5009.1 1903.88  5048.0 1909.61  5062.1 1911.89  5090.4 1917.87
  5104.5 1920.33  5118.7 1921.97  5132.8 1924.57  5143.4 1927.65  5147.0 1927.65
#Mann=3,-1,0
  4578.3    0.05       0  4987.9    0.05       0  4993.0    0.05       0
Bank Sta=4987.9,4993
Exp/Cntr=0.3,0.1

Type RM Length L Ch R = 1,6338,481,481,481
BEGIN DESCRIPTION:
Deadman 67 13.0
END DESCRIPTION:
XS GIS Cut Line= 3
      1646805.02      6844237.99      1646405.00      6844388.00
      1646305.01      6844787.97
#Sta/Elev= 30
  4579.8 1921.75  4595.0 1920.46  4611.9 1917.86  4650.1 1915.17  4705.3 1912.22
  4782.7 1910.44  4814.8 1909.04  4826.4 1909.61  4836.1 1908.95  4868.2 1908.44
  4911.8 1906.91  4931.4 1905.42  4936.7 1905.61  4961.6 1902.17  4967.0 1900.63
  4972.4 1900.44  4972.8 1899.94  4977.2 1899.94  4977.5 1900.44  4985.7 1900.61
  4997.2 1902.69  5037.9 1904.42  5161.6 1905.78  5190.0 1906.59  5231.2 1911.46
  5254.4 1915.94  5285.3 1920.04  5360.1 1924.00  5401.3 1929.18  5419.3 1930.37
#Mann=3,-1,0
  4579.8    0.05       0  4972.4    0.05       0  4977.5    0.05       0
Bank Sta=4972.4,4977.5
Exp/Cntr=0.3,0.1

Type RM Length L Ch R = 1,5857,417,417,417
BEGIN DESCRIPTION:
Deadman 67 12.0
END DESCRIPTION:
XS GIS Cut Line= 3
      1645754.98      6843787.97      1646005.00      6844188.00
      1646154.99      6844587.97
#Sta/Elev= 30
  4527.5 1943.50  4550.5 1939.62  4593.0 1934.52  4608.3 1933.92  4650.8 1929.35
  4687.3 1921.47  4745.1 1914.42  4781.7 1906.93  4818.2 1903.81  4839.4 1903.08
  4854.8 1900.88  4933.8 1900.71  4949.1 1898.54  4955.0 1899.31  4981.6 1897.07
  4982.1 1896.57  4989.7 1897.07  4996.3 1898.71  5014.4 1900.38  5039.3 1898.57
  5044.6 1899.18  5063.3 1897.78  5069.5 1899.43  5074.9 1898.34  5094.5 1903.12
  5099.8 1902.12  5255.6 1903.81  5356.1 1907.42  5386.4 1910.88  5426.4 1917.13
#Mann=3,-1,0
  4527.5    0.05       0  4981.6    0.05       0  4989.7    0.05       0
Bank Sta=4981.6,4989.7
Exp/Cntr=0.3,0.1

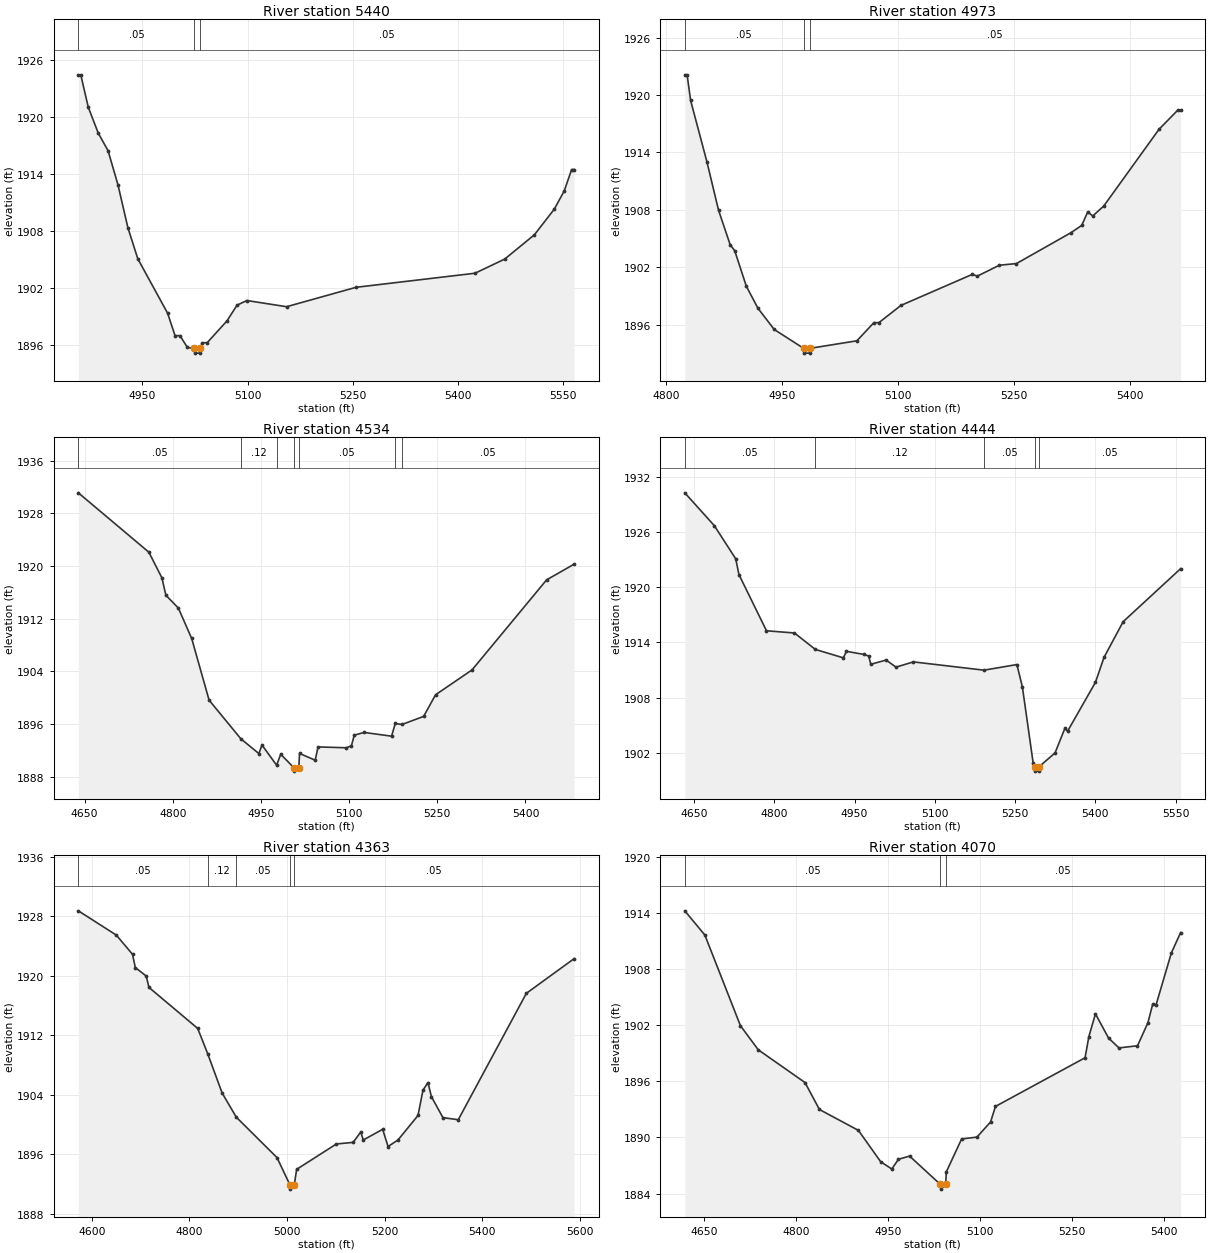
Type RM Length L Ch R = 1,5440,467,467,467
BEGIN DESCRIPTION:
Deadman 67 11.0
END DESCRIPTION:
XS GIS Cut Line= 3
      1645555.02      6844088.02      1645655.00      6844188.00
      1646055.01      6844588.01
#Sta/Elev= 30
  4858.6 1924.39  4862.1 1924.39  4872.7 1921.00  4886.9 1918.28  4901.0 1916.41
  4915.1 1912.83  4929.3 1908.31  4943.4 1905.05  4985.9 1899.33  4996.5 1896.97
  5003.5 1896.97  5014.1 1895.73  5024.2 1895.63  5024.7 1895.13  5031.8 1895.13
  5032.3 1895.63  5035.4 1896.22  5042.4 1896.23  5070.7 1898.53  5084.9 1900.17
  5099.0 1900.66  5155.6 1900.01  5254.6 1902.05  5424.3 1903.53  5466.7 1905.02
  5509.1 1907.58  5537.4 1910.27  5551.5 1912.18  5562.1 1914.43  5565.7 1914.43
#Mann=3,-1,0
  4858.6    0.05       0  5024.2    0.05       0  5032.3    0.05       0
Bank Sta=5024.2,5032.3
Exp/Cntr=0.3,0.1

Type RM Length L Ch R = 1,4973,439,439,439
BEGIN DESCRIPTION:
Deadman 67 10.0
END DESCRIPTION:
XS GIS Cut Line= 3
      1645304.98      6844487.99      1645455.00      6844588.00
      1645805.02      6844888.02
#Sta/Elev= 30
  4824.1 1922.10  4827.1 1922.10  4831.6 1919.43  4852.7 1913.01  4867.7 1907.96
  4882.7 1904.36  4888.7 1903.71  4903.7 1900.00  4918.8 1897.69  4939.8 1895.48
  4977.8 1893.51  4978.3 1893.01  4985.5 1893.01  4986.0 1893.51  5046.7 1894.30
  5068.6 1896.19  5075.2 1896.20  5103.7 1898.00  5195.9 1901.24  5202.5 1901.06
  5231.0 1902.20  5253.0 1902.37  5323.2 1905.58  5337.5 1906.36  5345.2 1907.76
  5351.8 1907.35  5366.0 1908.39  5437.4 1916.40  5462.1 1918.44  5465.4 1918.44
#Mann=3,-1,0
  4824.1    0.05       0  4977.8    0.05       0  4986.0    0.05       0
Bank Sta=4977.8,4986
Exp/Cntr=0.3,0.1

Type RM Length L Ch R = 1,4534,90,90,90
BEGIN DESCRIPTION:
Mapping XS 70526929
END DESCRIPTION:
XS GIS Cut Line= 5
      1645044.73      6844759.91      1645110.32      6844895.78
      1645248.58      6844961.40      1645349.34      6844994.20
      1645778.17      6845059.82
#Sta/Elev= 30
  4639.2 1931.13  4759.2 1922.11  4781.4 1918.21  4788.2 1915.56  4809.4 1913.62
  4832.1 1908.99  4861.7 1899.62  4915.8 1893.74  4946.4 1891.50  4951.7 1892.80
  4976.6 1889.73  4983.6 1891.39  5006.2 1889.33  5006.7 1888.83  5014.4 1889.33
  5015.6 1891.52  5042.2 1890.49  5047.1 1892.51  5095.3 1892.38  5103.8 1892.67
  5108.8 1894.30  5125.6 1894.71  5172.2 1894.14  5178.5 1896.07  5189.9 1895.92
  5226.8 1897.15  5247.0 1900.43  5309.2 1904.22  5436.0 1917.90  5482.9 1920.29
#Mann=7,-1,0
  4639.2    0.05       0  4915.8    0.12       0  4976.6    0.05       0
  5006.2    0.03       0  5014.4    0.05       0  5178.5    0.12       0
  5189.9    0.05       0
Bank Sta=5006.2,5014.4
Exp/Cntr=0.3,0.1

Type RM Length L Ch R = 1,4444,81,81,81
BEGIN DESCRIPTION:
Mapping XS 38b034d0
END DESCRIPTION:
XS GIS Cut Line= 6
      1644997.83      6844811.41      1645070.49      6844970.77
      1645133.76      6845003.58      1645227.49      6845043.41
      1645370.43      6845071.53      1645795.50      6845153.28
#Sta/Elev= 30
  4632.7 1930.24  4687.8 1926.68  4727.9 1923.07  4733.9 1921.36  4785.4 1915.25
  4837.7 1915.01  4876.8 1913.22  4929.1 1912.31  4934.8 1913.02  4967.4 1912.68
  4976.4 1912.51  4980.4 1911.61  5009.0 1912.07  5027.5 1911.30  5060.0 1911.87
  5191.9 1910.97  5253.5 1911.58  5263.7 1909.15  5284.0 1900.83  5287.1 1900.50
  5287.6 1900.00  5294.8 1900.00  5295.3 1900.50  5324.8 1901.98  5343.1 1904.64
  5348.2 1904.34  5400.2 1909.64  5416.4 1912.37  5452.1 1916.24  5559.5 1922.00
#Mann=5,-1,0
  4632.7    0.05       0  4876.8    0.12       0  5191.9    0.05       0
  5287.1    0.07       0  5295.3    0.05       0
Bank Sta=5287.1,5295.3
Exp/Cntr=0.3,0.1

Type RM Length L Ch R = 1,4363,293,293,293
BEGIN DESCRIPTION:
Mapping XS 00e04387
END DESCRIPTION:
XS GIS Cut Line= 4
      1644936.92      6844809.09      1645056.43      6845043.41
      1645241.55      6845130.12      1645778.13      6845242.59
#Sta/Elev= 30
  4572.5 1928.75  4650.4 1925.48  4683.5 1922.90  4689.2 1921.12  4711.5 1919.98
  4717.2 1918.44  4817.0 1912.93  4837.8 1909.47  4867.1 1904.23  4896.0 1900.99
  4979.5 1895.54  5006.5 1891.80  5007.0 1891.30  5014.7 1891.80  5019.7 1893.96
  5101.2 1897.38  5135.4 1897.59  5151.1 1898.99  5156.2 1897.91  5195.9 1899.35
  5207.0 1897.03  5227.4 1897.92  5268.3 1901.21  5278.5 1904.62  5288.7 1905.64
  5295.8 1903.74  5319.4 1900.92  5350.8 1900.64  5490.3 1917.65  5588.2 1922.32
#Mann=5,-1,0
  4572.5    0.05       0  4837.8    0.12       0  4896.0    0.05       0
  5006.5    0.05       0  5014.7    0.05       0
Bank Sta=5006.5,5014.7
Exp/Cntr=0.3,0.1

Type RM Length L Ch R = 1,4070,424,424,424
BEGIN DESCRIPTION:
Deadman 67 8.0
END DESCRIPTION:
XS GIS Cut Line= 3
      1645004.98      6845037.96      1645155.00      6845388.00
      1645554.97      6845537.99
#Sta/Elev= 30
  4618.9 1914.21  4651.6 1911.62  4709.6 1901.93  4738.6 1899.36  4814.8 1895.86
  4838.3 1892.98  4901.8 1890.75  4938.1 1887.40  4956.2 1886.62  4967.1 1887.66
  4985.2 1888.00  5035.5 1884.97  5036.0 1884.47  5044.0 1884.97  5045.1 1886.32
  5070.0 1889.83  5095.0 1890.03  5117.2 1891.65  5125.2 1893.31  5271.2 1898.51
  5277.4 1900.78  5288.1 1903.20  5309.5 1900.61  5326.4 1899.56  5356.6 1899.79
  5373.5 1902.23  5381.5 1904.26  5386.9 1904.17  5411.8 1909.71  5426.9 1911.89
#Mann=3,-1,0
  4618.9    0.05       0  5035.5    0.03       0  5044.0    0.05       0
Bank Sta=5035.5,5044
Exp/Cntr=0.3,0.1

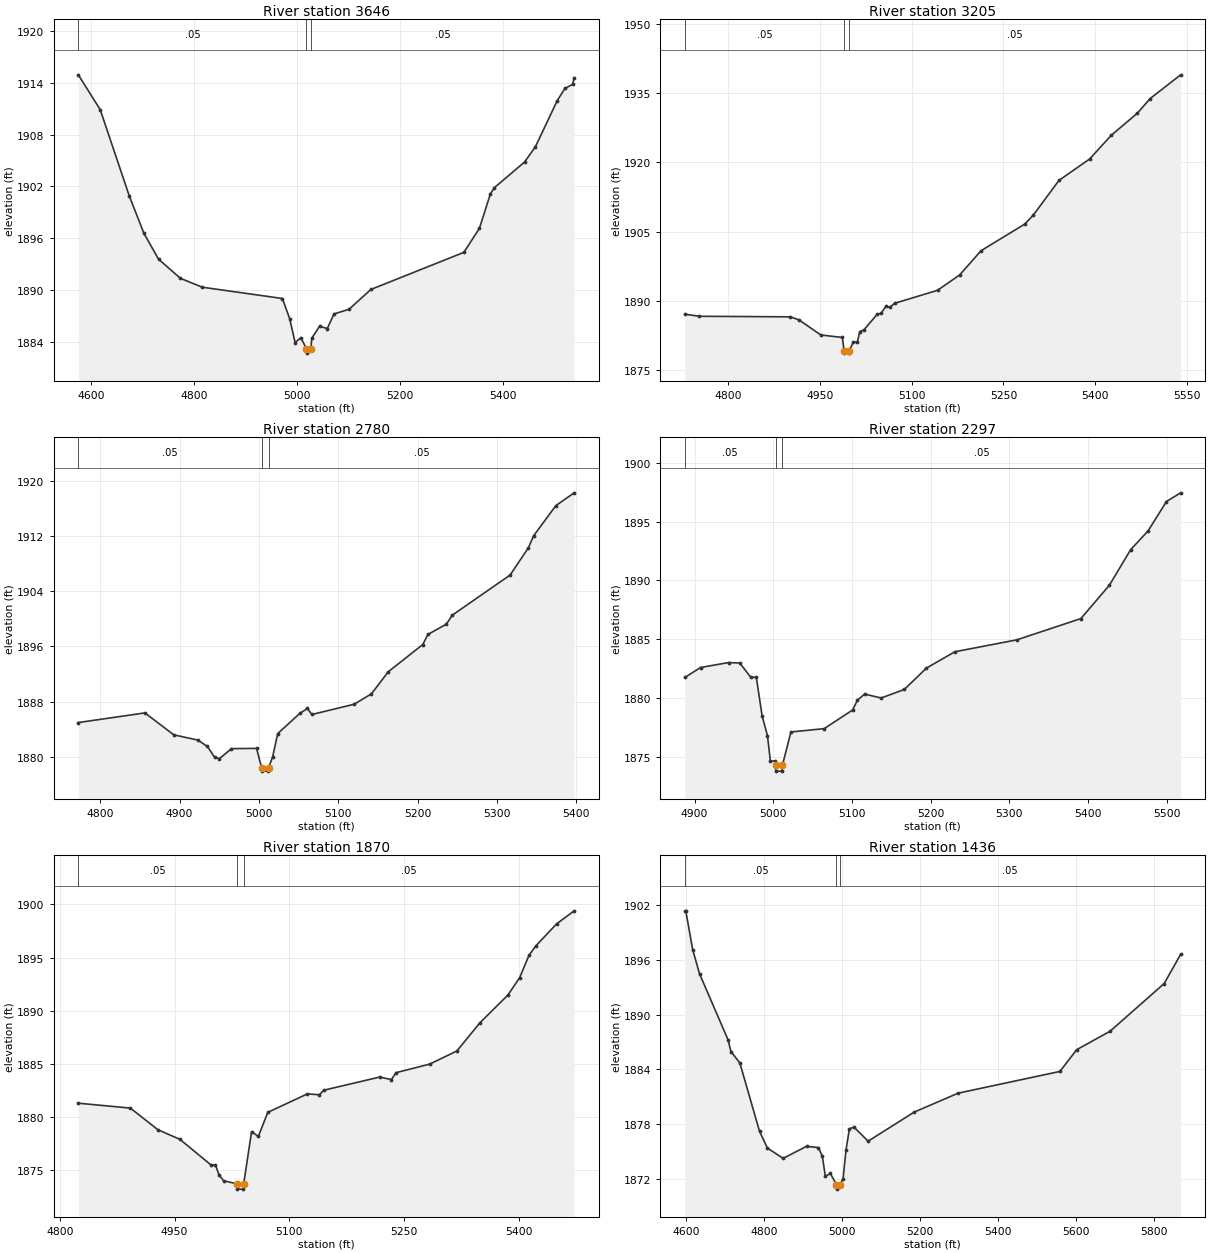
Type RM Length L Ch R = 1,3646,441,441,441
BEGIN DESCRIPTION:
Deadman 67 7.0
END DESCRIPTION:
XS GIS Cut Line= 3
      1644654.99      6845437.99      1644955.00      6845738.00
      1645404.64      6846033.09
#Sta/Elev= 30
  4576.0 1914.92  4618.4 1910.89  4675.0 1900.86  4703.3 1896.55  4731.6 1893.56
  4774.0 1891.34  4816.4 1890.31  4972.0 1889.00  4986.1 1886.66  4996.7 1883.89
  5007.8 1884.47  5018.6 1883.17  5019.1 1882.67  5027.3 1883.17  5028.9 1884.39
  5044.0 1885.78  5059.1 1885.52  5072.0 1887.21  5101.2 1887.75  5143.8 1890.05
  5324.2 1894.35  5354.4 1897.15  5375.5 1901.11  5383.0 1901.83  5441.8 1904.81
  5462.9 1906.58  5505.1 1911.91  5520.1 1913.34  5535.2 1913.82  5538.1 1914.59
#Mann=3,-1,0
  4576.0    0.05       0  5018.6    0.05       0  5027.3    0.05       0
Bank Sta=5018.6,5027.3
Exp/Cntr=0.3,0.1

Type RM Length L Ch R = 1,3205,425,425,425
BEGIN DESCRIPTION:
Deadman 67 6.0
END DESCRIPTION:
XS GIS Cut Line= 3
      1644613.12      6845935.96      1644805.00      6846138.00
      1645154.97      6846537.96
#Sta/Elev= 30
  4729.4 1887.16  4753.4 1886.70  4901.9 1886.58  4916.0 1885.92  4951.6 1882.66
  4986.8 1882.12  4989.7 1879.23  4990.2 1878.73  4997.9 1878.73  4998.4 1879.23
  5004.6 1881.13  5011.4 1881.13  5015.2 1883.37  5021.8 1883.74  5043.6 1887.10
  5050.3 1887.37  5057.9 1888.84  5064.5 1888.67  5072.1 1889.50  5142.3 1892.32
  5178.4 1895.63  5213.5 1900.89  5284.7 1906.63  5298.9 1908.60  5340.7 1916.09
  5391.0 1920.74  5426.1 1925.84  5468.8 1930.63  5489.7 1933.79  5539.5 1938.93
#Mann=3,-1,0
  4729.4    0.05       0  4989.7    0.05       0  4998.4    0.05       0
Bank Sta=4989.7,4998.4
Exp/Cntr=0.3,0.1

Type RM Length L Ch R = 1,2780,483,483,483
BEGIN DESCRIPTION:
Deadman 67 5.0
END DESCRIPTION:
XS GIS Cut Line= 3
      1644335.38      6846151.29      1644455.00      6846338.00
      1644655.02      6846688.04
#Sta/Elev= 30
  4772.4 1884.96  4856.3 1886.36  4892.7 1883.18  4922.9 1882.42  4935.0 1881.50
  4944.2 1879.91  4950.2 1879.72  4965.4 1881.17  4997.0 1881.21  5003.4 1878.41
  5003.9 1877.91  5011.7 1877.91  5012.2 1878.41  5017.2 1879.94  5023.7 1883.36
  5051.7 1886.30  5061.1 1887.00  5066.8 1886.13  5120.1 1887.62  5141.7 1889.12
  5163.3 1892.36  5206.5 1896.28  5213.0 1897.75  5236.0 1899.22  5243.9 1900.56
  5316.6 1906.37  5339.7 1910.34  5346.1 1912.05  5374.2 1916.44  5397.3 1918.30
#Mann=3,-1,0
  4772.4    0.05       0  5003.4    0.05       0  5012.2    0.05       0
Bank Sta=5003.4,5012.2
Exp/Cntr=0.3,0.1

Type RM Length L Ch R = 1,2297,427,427,427
BEGIN DESCRIPTION:
Deadman 67 4.0
END DESCRIPTION:
XS GIS Cut Line= 3
      1643929.11      6846255.42      1644005.00      6846338.00
      1644286.78      6846772.83
#Sta/Elev= 30
  4887.6 1881.75  4907.6 1882.60  4943.3 1883.02  4957.5 1882.98  4971.7 1881.75
  4978.5 1881.78  4985.9 1878.48  4992.7 1876.80  4996.4 1874.65  5002.7 1874.65
  5002.9 1874.29  5003.4 1873.79  5011.2 1873.79  5011.7 1874.29  5022.5 1877.12
  5064.7 1877.40  5101.0 1878.99  5107.0 1879.82  5116.1 1880.34  5137.2 1880.01
  5166.6 1880.73  5194.6 1882.54  5230.9 1883.94  5309.6 1884.95  5391.1 1886.76
  5427.3 1889.59  5454.4 1892.62  5476.4 1894.20  5499.9 1896.71  5517.9 1897.45
#Mann=3,-1,0
  4887.6    0.05       0  5002.9    0.05       0  5011.7    0.05       0
Bank Sta=5002.9,5011.7
Exp/Cntr=0.3,0.1

Type RM Length L Ch R = 1,1870,434,434,434
BEGIN DESCRIPTION:
Deadman 67 3.0
END DESCRIPTION:
XS GIS Cut Line= 3
      1643706.88      6846491.52      1643805.00      6846638.00
      1644205.00      6846888.00
#Sta/Elev= 30
  4824.3 1881.31  4892.3 1880.85  4928.4 1878.81  4957.1 1877.91  4997.6 1875.51
  5003.5 1875.51  5008.3 1874.54  5014.2 1874.02  5031.6 1873.73  5032.1 1873.23
  5039.9 1873.23  5040.4 1873.73  5050.7 1878.62  5059.6 1878.19  5071.9 1880.45
  5123.8 1882.19  5139.2 1882.10  5145.1 1882.53  5218.2 1883.77  5233.5 1883.53
  5239.4 1884.18  5283.6 1884.99  5319.0 1886.22  5349.1 1888.87  5385.6 1891.47
  5401.0 1893.11  5413.3 1895.22  5422.2 1896.10  5449.3 1898.17  5472.3 1899.40
#Mann=3,-1,0
  4824.3    0.05       0  5031.6    0.05       0  5040.4    0.05       0
Bank Sta=5031.6,5040.4
Exp/Cntr=0.3,0.1

Type RM Length L Ch R = 1,1436,391,391,391
BEGIN DESCRIPTION:
Deadman 67 2.0
END DESCRIPTION:
XS GIS Cut Line= 3
      1643355.00      6846337.98      1643405.00      6846738.00
      1643599.50      6847583.79
#Sta/Elev= 30
  4596.8 1901.37  4599.3 1901.37  4617.0 1897.13  4634.6 1894.47  4707.7 1887.24
  4715.2 1885.95  4737.9 1884.71  4788.3 1877.23  4808.5 1875.39  4848.8 1874.26
  4909.2 1875.58  4939.5 1875.44  4949.5 1874.47  4957.1 1872.28  4969.7 1872.62
  4985.5 1871.39  4986.0 1870.89  4994.3 1871.39  5002.5 1872.03  5010.2 1875.23
  5018.8 1877.50  5030.7 1877.68  5066.7 1876.14  5184.6 1879.32  5297.5 1881.40
  5558.4 1883.78  5601.3 1886.16  5686.9 1888.18  5825.7 1893.41  5867.8 1896.60
#Mann=3,-1,0
  4596.8    0.05       0  4985.5    0.05       0  4994.3    0.05       0
Bank Sta=4985.5,4994.3
Exp/Cntr=0.3,0.1