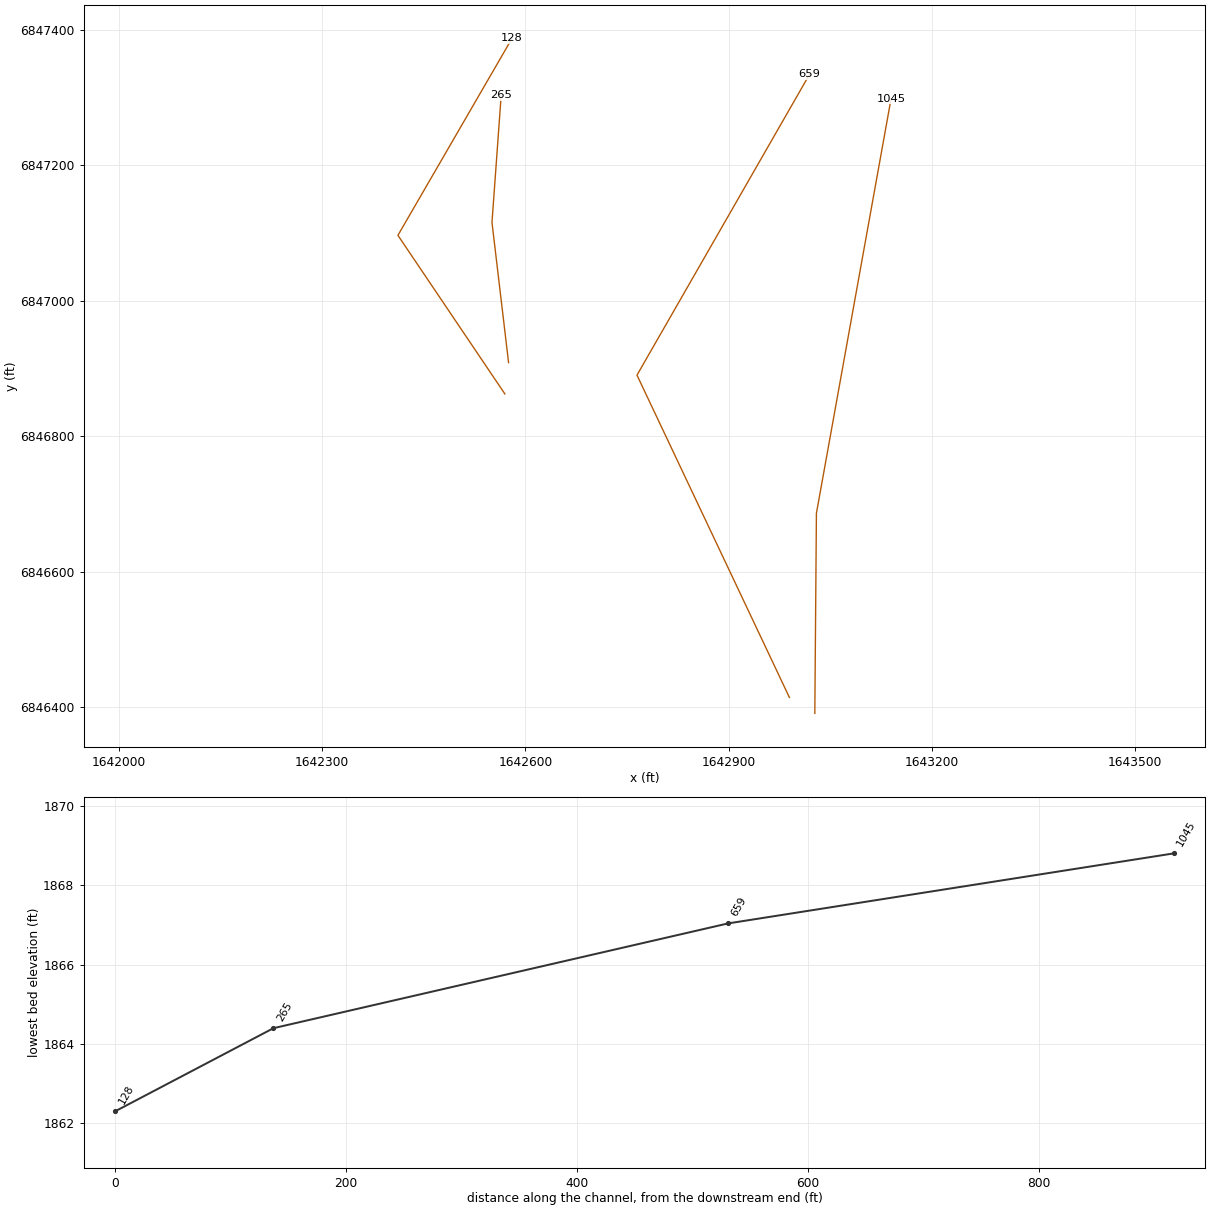
HEC-RAS study Deadman 67.prj: Deadman 67 Base Level Engineering

--- Deadman 67.g01 (geometry) --- (continued)

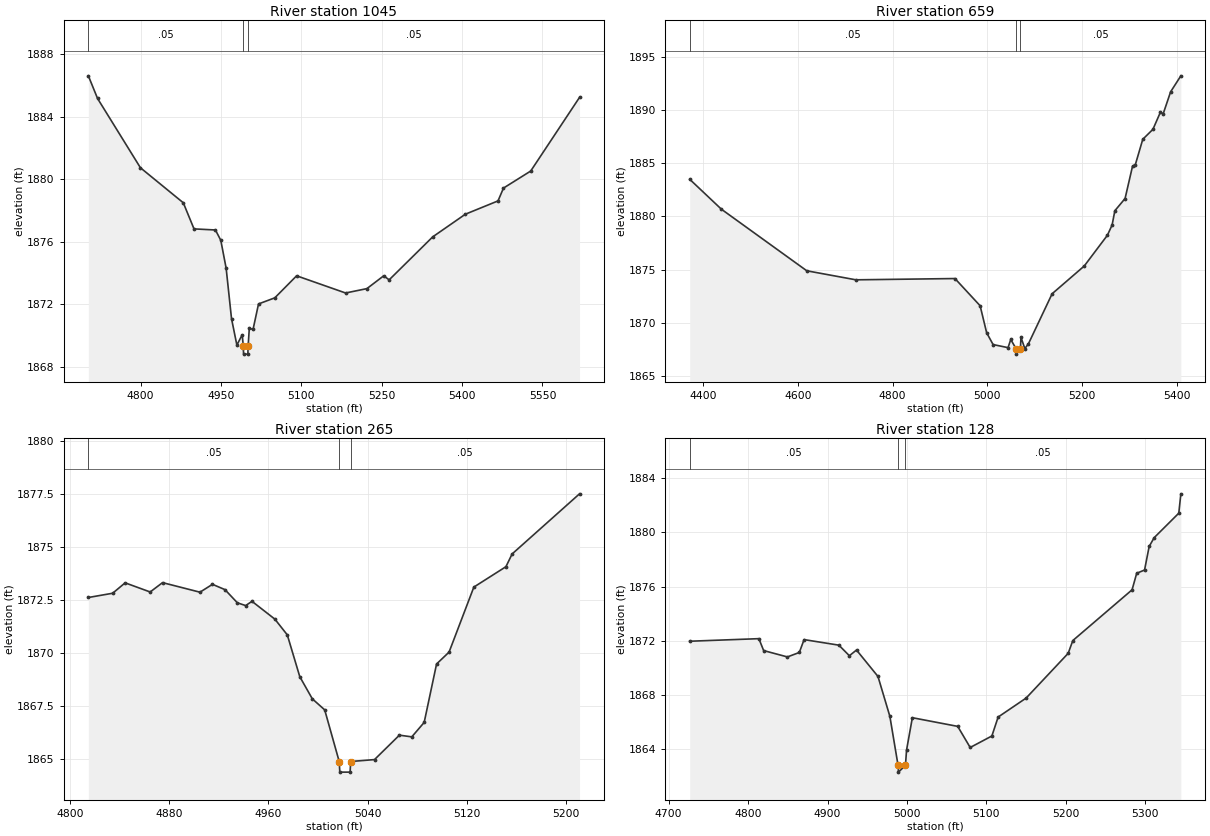
Type RM Length L Ch R = 1,1045,386,386,386
BEGIN DESCRIPTION:
Mapping XS 700730d9
END DESCRIPTION:
XS GIS Cut Line= 3
      1643027.09      6846390.81      1643029.44      6846686.10
      1643139.57      6847297.66
#Sta/Elev= 30
  4702.5 1886.61  4719.7 1885.16  4799.7 1880.73  4879.7 1878.49  4899.7 1876.82
  4939.7 1876.75  4949.7 1876.09  4959.7 1874.30  4969.7 1871.08  4979.7 1869.39
  4989.7 1870.05  4991.7 1869.31  4992.2 1868.81  5000.2 1868.81  5000.7 1869.31
  5002.9 1870.46  5009.9 1870.39  5020.1 1872.02  5050.5 1872.41  5091.2 1873.82
  5182.6 1872.72  5222.4 1873.00  5253.8 1873.82  5263.9 1873.56  5345.2 1876.31
  5406.2 1877.76  5467.1 1878.61  5477.3 1879.43  5528.1 1880.52  5619.2 1885.23
#Mann=3,-1,0
  4702.5    0.05       0  4991.7    0.03       0  5000.7    0.05       0
Bank Sta=4991.7,5000.7
Exp/Cntr=0.3,0.1

Type RM Length L Ch R = 1,659,394,394,394
BEGIN DESCRIPTION:
Mapping XS f5f96814
END DESCRIPTION:
XS GIS Cut Line= 3
      1642989.61      6846414.24      1642764.64      6846889.97
      1643019.40      6847334.04
#Sta/Elev= 30
  4371.0 1883.49  4438.1 1880.67  4618.5 1874.88  4722.3 1874.03  4931.7 1874.15
  4984.9 1871.59  4998.7 1869.05  5012.3 1867.94  5043.9 1867.65  5049.7 1868.42
  5060.9 1867.54  5061.4 1867.04  5070.1 1867.54  5071.2 1868.63  5079.4 1867.56
  5087.0 1868.01  5137.1 1872.72  5205.0 1875.33  5253.9 1878.22  5263.9 1879.19
  5269.7 1880.53  5291.3 1881.68  5307.1 1884.73  5312.9 1884.85  5328.7 1887.25
  5350.2 1888.19  5366.1 1889.81  5371.8 1889.64  5387.6 1891.72  5409.2 1893.22
#Mann=3,-1,0
  4371.0    0.05       0  5060.9    0.05       0  5070.1    0.05       0
Bank Sta=5060.9,5070.1
Exp/Cntr=0.3,0.1

Type RM Length L Ch R = 1,265,137,137,137
BEGIN DESCRIPTION:
Mapping XS 4c6c1e22
END DESCRIPTION:
XS GIS Cut Line= 3
      1642575.13      6846908.49      1642550.63      6847115.37
      1642564.23      6847303.06
#Sta/Elev= 30
  4814.6 1872.61  4834.2 1872.81  4844.3 1873.30  4864.5 1872.87  4874.5 1873.31
  4904.7 1872.86  4914.8 1873.23  4924.9 1872.98  4934.9 1872.36  4941.6 1872.23
  4946.7 1872.43  4965.2 1871.59  4975.2 1870.85  4985.3 1868.88  4995.4 1867.84
  5005.4 1867.32  5017.1 1864.89  5017.6 1864.39  5025.9 1864.39  5026.4 1864.89
  5045.6 1864.98  5065.7 1866.13  5075.7 1866.05  5085.7 1866.73  5095.7 1869.48
  5105.8 1870.04  5125.8 1873.10  5151.7 1874.06  5156.7 1874.66  5211.1 1877.49
#Mann=3,-1,0
  4814.6    0.05       0  5017.1    0.05       0  5026.4    0.05       0
Bank Sta=5017.1,5026.4
Exp/Cntr=0.3,0.1

Type RM Length L Ch R = 1,128,0,0,0
BEGIN DESCRIPTION:
Deadman 67 1.0
END DESCRIPTION:
XS GIS Cut Line= 3
      1642569.66      6846862.27      1642411.82      6847096.31
      1642580.27      6847387.04
#Sta/Elev= 30
  4726.5 1871.96  4813.6 1872.15  4819.6 1871.27  4849.5 1870.80  4864.5 1871.13
  4870.5 1872.08  4914.3 1871.67  4927.5 1870.89  4936.5 1871.31  4963.5 1869.36
  4978.5 1866.41  4988.8 1862.79  4989.3 1862.29  4998.1 1862.79  4999.5 1863.92
  5006.8 1866.31  5063.9 1865.67  5079.6 1864.11  5106.9 1864.96  5114.8 1866.36
  5150.0 1867.76  5203.0 1871.07  5208.8 1872.01  5283.4 1875.76  5289.2 1876.98
  5299.1 1877.22  5304.9 1878.96  5311.2 1879.61  5342.2 1881.42  5344.8 1882.85
#Mann=3,-1,0
  4726.5    0.05       0  4988.8    0.05       0  4998.1    0.05       0
Bank Sta=4988.8,4998.1
Exp/Cntr=0.3,0.1

Chan Stop Cuts=-1