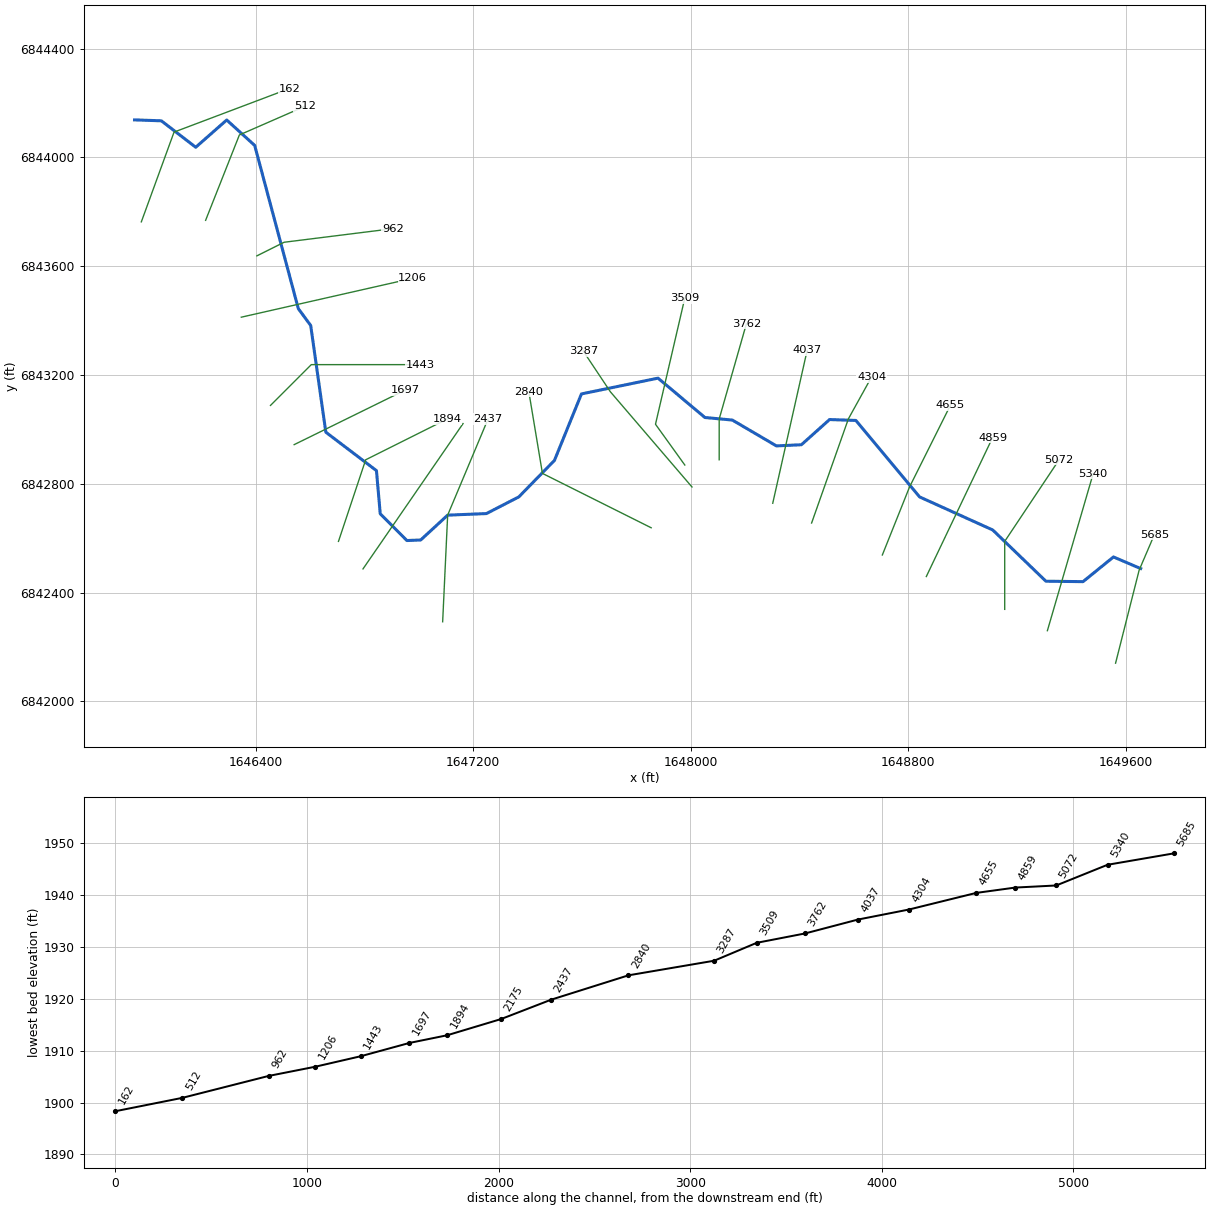
--- Deadman 68.prj (project) ---

Proj Title=Deadman 68 Base Level Engineering
Current Plan=p01
Default Exp/Contr=0.3,0.1
English Units
Geom File=g01
Flow File=f01
Plan File=p01
Y Axis Title=Elevation
X Axis Title(PF)=Main Channel Distance
X Axis Title(XS)=Station
BEGIN DESCRIPTION:
Deadman 68
END DESCRIPTION:
DSS Export Rating Curves= 0
DSS Export Rating Curve Sorted= 0
DSS Export Volume Flow Curves= 0
DXF OffsetX= 0
DXF OffsetY= 0
DXF ScaleX= 1
DXF ScaleY= 10

--- Deadman 68.p01 (plan) ---

Plan Title=Multiple Run
Short Identifier=Multiple
Geom File=g01
Flow File=f01
Subcritical Flow
K Sum by GR= 0
Std Step Tol= 0.01
Critical Tol= 0.01
Num of Std Step Trials= 20
Max Error Tol= 0.3
Flow Tol Ratio= 0.001
Split Flow NTrial= 30
Split Flow Tol= 0.02
Split Flow Ratio= 0.02
Log Output Level= 0
Friction Slope Method= 1
Unsteady Friction Slope Method= 2
Unsteady Bridges Friction Slope Method= 1
Parabolic Critical Depth
Global Vel Dist=  1 , 1 , 1
Global Log Level= 0
CheckData=True
Encroach Param= -1, 0, 0, 0
BEGIN DESCRIPTION:
Multiple Run
END DESCRIPTION:

--- Deadman 68.f01 (steady flow) ---

Flow Title=Multiple
Program Version=4.10
Number of Profiles= 7
Profile Names=10-year,25-year,50-year,1pct_min,100-year,1pct_plu,500-year
River Rch & RM=Deadman 68,Reach-1         ,5685
     194     262     317     191     382     761     560
River Rch & RM=Deadman 68,Reach-1         ,5340
     270     374     461     282     563    1124     854
Boundary for River Rch & Prof#=Deadman 68,Reach-1         , 1
Up Type= 0
Dn Type= 3
Dn Slope=0.009
Boundary for River Rch & Prof#=Deadman 68,Reach-1         , 2
Up Type= 0
Dn Type= 3
Dn Slope=0.009
Boundary for River Rch & Prof#=Deadman 68,Reach-1         , 3
Up Type= 0
Dn Type= 3
Dn Slope=0.009
Boundary for River Rch & Prof#=Deadman 68,Reach-1         , 4
Up Type= 0
Dn Type= 3
Dn Slope=0.009
Boundary for River Rch & Prof#=Deadman 68,Reach-1         , 5
Up Type= 0
Dn Type= 3
Dn Slope=0.009
Boundary for River Rch & Prof#=Deadman 68,Reach-1         , 6
Up Type= 0
Dn Type= 3
Dn Slope=0.009
Boundary for River Rch & Prof#=Deadman 68,Reach-1         , 7
Up Type= 0
Dn Type= 3
Dn Slope=0.009
DSS Import GetInterval= 0
DSS Import GetPeak= 0
DSS Import FillOption= 0

--- Deadman 68.g01 (geometry) ---

Geom Title=Existing Conditions

River Reach=Deadman 68,Reach-1
Reach XY= 30
      1649655.00      6842488.00      1649555.00      6842530.73
      1649443.05      6842439.91      1649306.47      6842441.53
      1649111.06      6842629.86      1648841.79      6842751.62
      1648607.67      6843032.71      1648510.90      6843036.03
      1648407.42      6842943.41      1648315.55      6842939.08
      1648153.41      6843034.17      1648052.57      6843043.52
      1647880.11      6843188.32      1647598.50      6843130.27
      1647499.17      6842885.70      1647368.22      6842751.62
      1647249.07      6842690.25      1647106.47      6842684.44
      1647007.28      6842593.08      1646956.63      6842591.09
      1646858.54      6842689.45      1646844.65      6842848.12
      1646658.54      6842989.46      1646602.74      6843382.06
      1646557.27      6843443.94      1646396.87      6844044.08
      1646293.99      6844137.61      1646180.08      6844037.39
      1646053.59      6844134.60      1645955.00      6844138.00

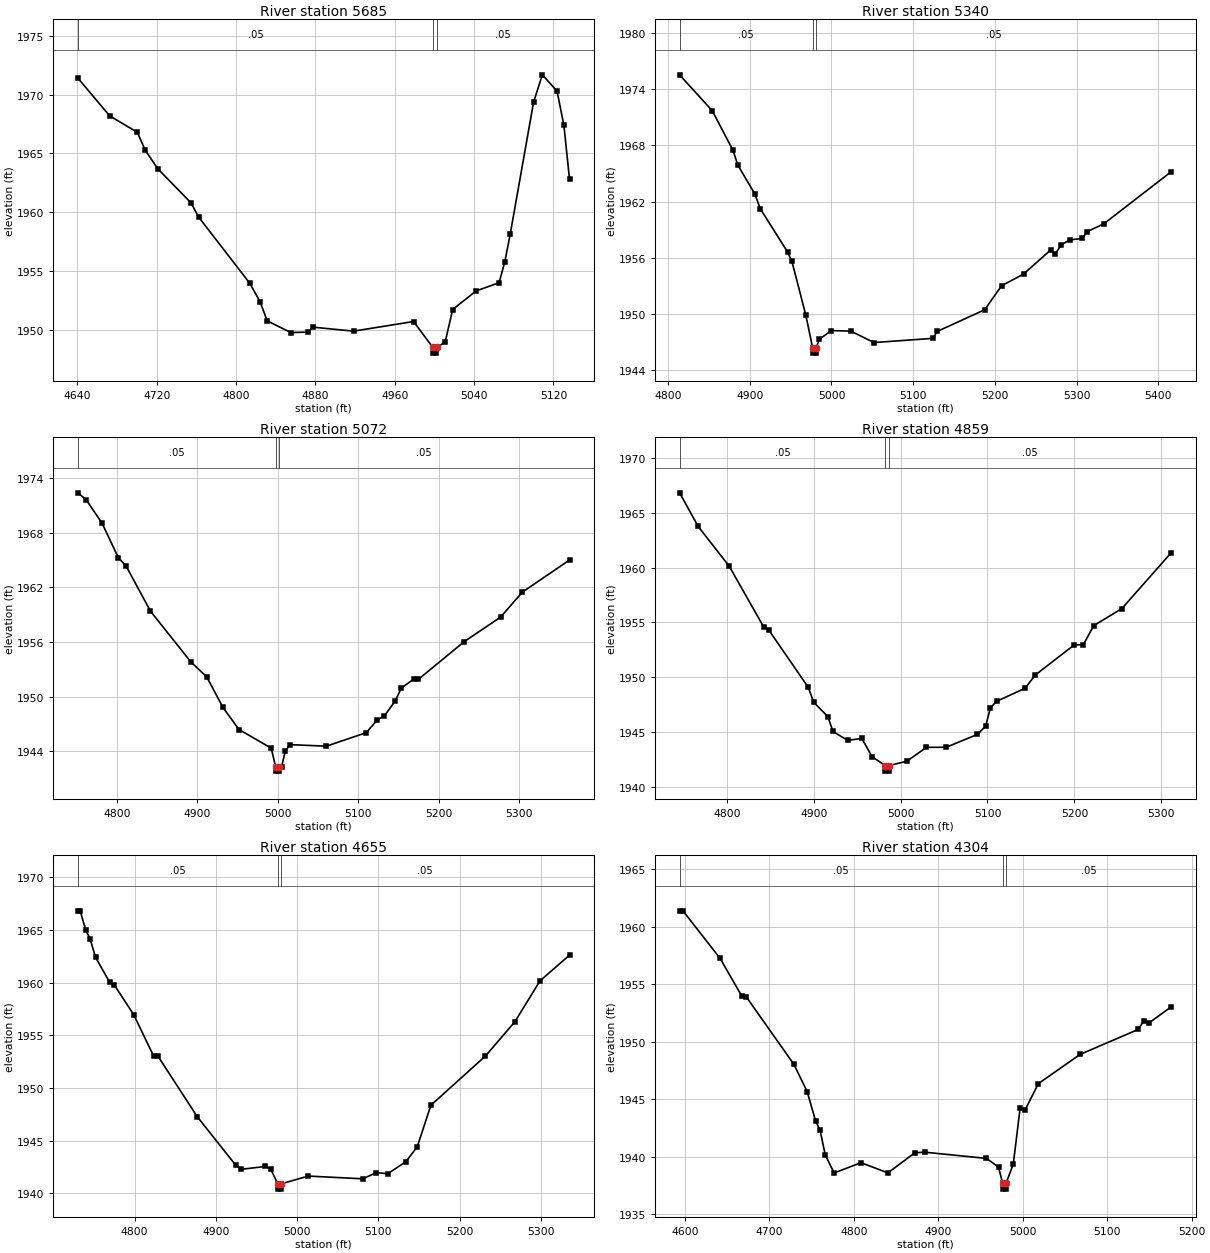
Type RM Length L Ch R = 1,5685,345,345,345
BEGIN DESCRIPTION:
Deadman 68 12.0
END DESCRIPTION:
XS GIS Cut Line= 3
      1649562.68      6842140.06      1649649.37      6842482.14
      1649705.55      6842613.22
#Sta/Elev= 30
  4640.7 1971.39  4672.6 1968.19  4700.5 1966.79  4708.4 1965.28  4721.1 1963.69
  4754.6 1960.79  4762.4 1959.57  4813.9 1953.94  4824.3 1952.37  4831.4 1950.75
  4855.2 1949.75  4872.4 1949.79  4877.5 1950.21  4918.5 1949.87  4979.0 1950.69
  4998.3 1948.50  4998.6 1948.00  5002.1 1948.00  5002.3 1948.50  5010.8 1948.92
  5018.4 1951.71  5042.0 1953.29  5065.2 1953.99  5071.0 1955.78  5076.5 1958.16
  5100.0 1969.36  5108.8 1971.68  5123.6 1970.30  5130.5 1967.40  5136.2 1962.82
#Mann=3,-1,0
  4640.7    0.05       0  4998.3    0.03       0  5002.3    0.05       0
Bank Sta=4998.3,5002.3
Exp/Cntr=0.3,0.1

Type RM Length L Ch R = 1,5340,268,268,268
BEGIN DESCRIPTION:
Mapping XS 0402c580
END DESCRIPTION:
XS GIS Cut Line= 2
      1649311.94      6842259.56      1649480.33      6842837.21
#Sta/Elev= 30
  4814.1 1975.55  4854.1 1971.71  4879.4 1967.49  4885.4 1965.90  4906.2 1962.82
  4912.9 1961.24  4946.4 1956.60  4951.6 1955.61  4968.7 1949.84  4977.1 1946.31
  4977.4 1945.81  4980.9 1945.81  4981.1 1946.31  4985.1 1947.29  5000.0 1948.22
  5023.8 1948.16  5052.1 1946.94  5124.3 1947.39  5129.5 1948.13  5187.5 1950.44
  5208.3 1953.01  5235.2 1954.26  5268.6 1956.85  5273.9 1956.39  5281.2 1957.37
  5291.6 1957.91  5307.3 1958.07  5312.6 1958.78  5333.3 1959.62  5415.8 1965.19
#Mann=3,-1,0
  4814.1    0.05       0  4977.1    0.05       0  4981.1    0.05       0
Bank Sta=4977.1,4981.1
Exp/Cntr=0.3,0.1

Type RM Length L Ch R = 1,5072,213,213,213
BEGIN DESCRIPTION:
Deadman 68 11.0
END DESCRIPTION:
XS GIS Cut Line= 3
      1649155.00      6842338.00      1649155.00      6842588.00
      1649355.03      6842888.04
#Sta/Elev= 30
  4751.7 1972.39  4761.7 1971.65  4781.7 1969.04  4801.7 1965.28  4811.7 1964.31
  4841.7 1959.40  4891.7 1953.84  4911.7 1952.16  4931.7 1948.83  4951.7 1946.39
  4991.7 1944.35  4997.2 1942.32  4997.4 1941.82  5000.9 1941.82  5001.2 1942.32
  5004.7 1942.32  5009.2 1944.03  5015.2 1944.73  5060.3 1944.56  5109.9 1946.05
  5123.4 1947.44  5132.4 1947.89  5145.9 1949.55  5153.4 1950.94  5168.5 1951.92
  5174.5 1951.90  5231.6 1956.05  5276.6 1958.73  5303.7 1961.48  5362.3 1965.01
#Mann=3,-1,0
  4751.7    0.05       0  4997.2    0.05       0  5001.2    0.05       0
Bank Sta=4997.2,5001.2
Exp/Cntr=0.3,0.1

Type RM Length L Ch R = 1,4859,204,204,204
BEGIN DESCRIPTION:
Mapping XS 02354515
END DESCRIPTION:
XS GIS Cut Line= 2
      1648866.69      6842458.69      1649110.22      6842969.18
#Sta/Elev= 30
  4745.7 1966.83  4767.1 1963.76  4802.9 1960.12  4842.7 1954.55  4848.2 1954.32
  4893.6 1949.09  4900.0 1947.72  4916.3 1946.39  4922.2 1945.04  4939.0 1944.23
  4955.4 1944.40  4967.2 1942.74  4982.4 1941.92  4982.6 1941.42  4986.1 1941.42
  4986.4 1941.92  5007.1 1942.32  5029.8 1943.59  5052.5 1943.60  5088.4 1944.77
  5097.9 1945.53  5103.4 1947.22  5110.6 1947.80  5143.2 1948.98  5154.9 1950.19
  5199.7 1952.94  5210.3 1952.97  5222.4 1954.71  5254.6 1956.26  5311.3 1961.35
#Mann=3,-1,0
  4745.7    0.05       0  4982.4    0.05       0  4986.4    0.05       0
Bank Sta=4982.4,4986.4
Exp/Cntr=0.3,0.1

Type RM Length L Ch R = 1,4655,351,351,351
BEGIN DESCRIPTION:
Deadman 68 10.0
END DESCRIPTION:
XS GIS Cut Line= 3
      1648704.99      6842537.97      1648805.00      6842788.00
      1648955.00      6843088.00
#Sta/Elev= 30
  4730.4 1966.82  4733.1 1966.82  4739.9 1964.99  4745.2 1964.18  4752.0 1962.40
  4769.5 1960.02  4774.9 1959.80  4799.1 1956.94  4823.3 1953.05  4828.7 1953.03
  4877.2 1947.26  4924.3 1942.68  4931.0 1942.27  4960.7 1942.54  4967.4 1942.31
  4976.2 1940.89  4976.4 1940.39  4979.9 1940.39  4980.2 1940.89  5013.7 1941.63
  5080.8 1941.37  5097.5 1941.96  5111.5 1941.85  5133.9 1943.00  5147.8 1944.42
  5164.6 1948.36  5231.7 1953.03  5268.0 1956.30  5298.8 1960.17  5335.1 1962.61
#Mann=3,-1,0
  4730.4    0.05       0  4976.2    0.05       0  4980.2    0.05       0
Bank Sta=4976.2,4980.2
Exp/Cntr=0.3,0.1

Type RM Length L Ch R = 1,4304,267,267,267
BEGIN DESCRIPTION:
Deadman 68 9.0
END DESCRIPTION:
XS GIS Cut Line= 3
      1648444.88      6842655.52      1648580.12      6843038.54
      1648665.17      6843192.17
#Sta/Elev= 30
  4593.8 1961.37  4597.8 1961.37  4641.7 1957.24  4667.3 1953.98  4672.6 1953.91
  4729.2 1948.02  4744.9 1945.65  4754.8 1943.10  4760.1 1942.32  4766.1 1940.18
  4776.7 1938.59  4808.5 1939.49  4840.4 1938.60  4872.2 1940.35  4883.8 1940.40
  4957.0 1939.86  4971.3 1939.11  4976.2 1937.69  4976.5 1937.19  4980.0 1937.19
  4980.2 1937.69  4988.8 1939.38  4996.9 1944.24  5002.5 1944.04  5018.5 1946.36
  5068.0 1948.90  5136.5 1951.06  5143.3 1951.81  5149.0 1951.61  5175.6 1953.02
#Mann=3,-1,0
  4593.8    0.05       0  4976.2    0.05       0  4980.2    0.05       0
Bank Sta=4976.2,4980.2
Exp/Cntr=0.3,0.1

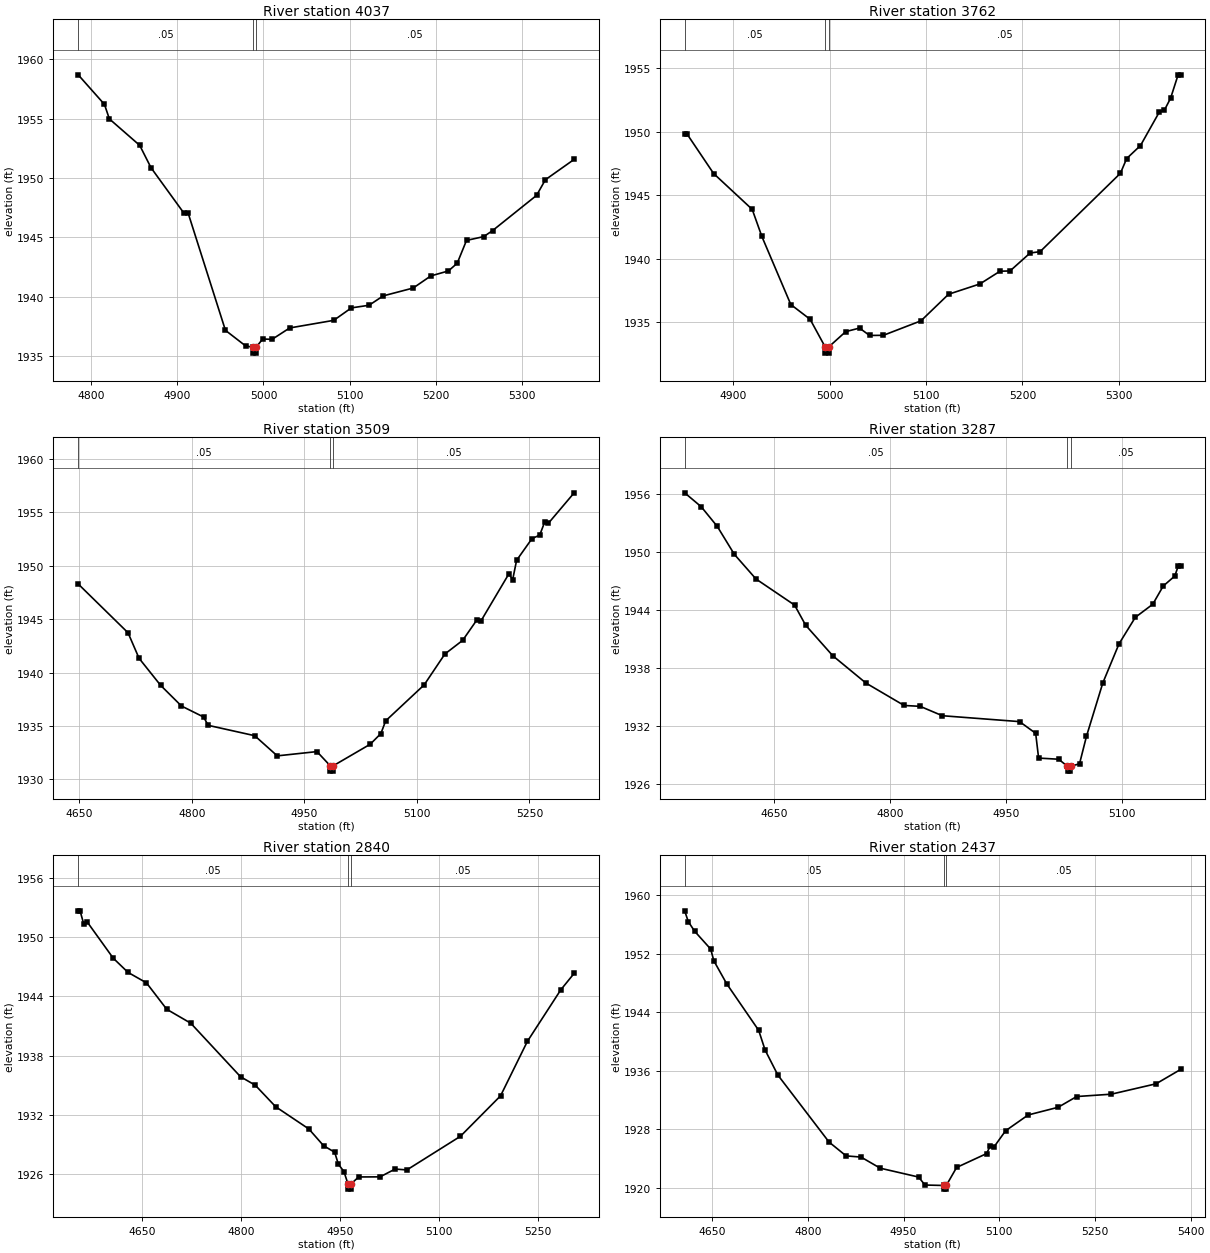
Type RM Length L Ch R = 1,4037,275,275,275
BEGIN DESCRIPTION:
Mapping XS aeb4d120
END DESCRIPTION:
XS GIS Cut Line= 2
      1648301.95      6842728.21      1648428.48      6843290.55
#Sta/Elev= 30
  4784.7 1958.68  4815.2 1956.19  4820.9 1954.97  4856.2 1952.74  4869.3 1950.86
  4907.4 1947.05  4912.5 1947.03  4955.8 1937.17  4979.2 1935.86  4987.5 1935.75
  4987.7 1935.25  4991.2 1935.25  4991.5 1935.75  4999.1 1936.44  5010.0 1936.41
  5030.5 1937.37  5081.7 1938.01  5102.2 1939.06  5122.7 1939.28  5139.2 1940.07
  5174.0 1940.73  5194.5 1941.75  5215.0 1942.17  5225.2 1942.82  5236.0 1944.74
  5256.0 1945.06  5266.2 1945.56  5317.4 1948.53  5327.7 1949.85  5361.1 1951.56
#Mann=3,-1,0
  4784.7    0.05       0  4987.5    0.05       0  4991.5    0.05       0
Bank Sta=4987.5,4991.5
Exp/Cntr=0.3,0.1

Type RM Length L Ch R = 1,3762,253,253,253
BEGIN DESCRIPTION:
Deadman 68 8.0
END DESCRIPTION:
XS GIS Cut Line= 3
      1648105.00      6842888.02      1648105.00      6843038.00
      1648205.00      6843388.01
#Sta/Elev= 30
  4849.9 1949.80  4852.4 1949.80  4879.9 1946.70  4919.9 1943.88  4929.9 1941.75
  4959.9 1936.40  4979.9 1935.24  4995.4 1933.08  4995.6 1932.58  4999.1 1932.58
  4999.4 1933.08  5016.8 1934.27  5031.1 1934.55  5041.5 1933.97  5055.8 1933.98
  5094.8 1935.12  5123.4 1937.21  5155.9 1938.02  5176.7 1939.02  5187.1 1939.04
  5207.9 1940.45  5218.3 1940.56  5301.5 1946.72  5308.0 1947.88  5322.3 1948.90
  5341.8 1951.53  5347.0 1951.67  5353.5 1952.62  5361.3 1954.46  5363.9 1954.46
#Mann=3,-1,0
  4849.9    0.05       0  4995.4    0.05       0  4999.4    0.05       0
Bank Sta=4995.4,4999.4
Exp/Cntr=0.3,0.1

Type RM Length L Ch R = 1,3509,222,222,222
BEGIN DESCRIPTION:
Mapping XS 66f41832
END DESCRIPTION:
XS GIS Cut Line= 3
      1647978.56      6842868.80      1647870.78      6843018.77
      1647978.57      6843482.73
#Sta/Elev= 30
  4648.6 1948.30  4715.0 1943.73  4729.7 1941.34  4758.4 1938.81  4786.2 1936.87
  4815.7 1935.84  4821.8 1935.06  4883.8 1934.09  4913.9 1932.20  4966.8 1932.60
  4984.5 1931.27  4984.7 1930.77  4988.2 1930.77  4988.5 1931.27  5037.8 1933.29
  5052.0 1934.29  5058.4 1935.48  5109.7 1938.85  5137.3 1941.74  5161.0 1943.02
  5179.9 1944.93  5185.0 1944.79  5222.5 1949.24  5227.7 1948.72  5232.9 1950.52
  5253.4 1952.55  5263.7 1952.88  5270.3 1954.10  5275.4 1954.00  5309.6 1956.84
#Mann=3,-1,0
  4648.6    0.05       0  4984.5    0.05       0  4988.5    0.05       0
Bank Sta=4984.5,4988.5
Exp/Cntr=0.3,0.1

Type RM Length L Ch R = 1,3287,447,447,447
BEGIN DESCRIPTION:
Deadman 68 7.0
END DESCRIPTION:
XS GIS Cut Line= 3
      1648004.98      6842788.03      1647705.00      6843138.00
      1647605.01      6843287.99
#Sta/Elev= 30
  4534.1 1956.10  4555.5 1954.66  4576.3 1952.62  4598.3 1949.74  4626.3 1947.19
  4676.2 1944.49  4690.5 1942.41  4725.6 1939.25  4768.4 1936.43  4817.8 1934.11
  4838.6 1934.02  4867.2 1933.05  4967.1 1932.44  4987.9 1931.23  4991.7 1928.67
  5017.6 1928.55  5029.0 1927.82  5029.3 1927.32  5032.8 1927.32  5033.1 1927.82
  5044.6 1928.08  5053.6 1930.93  5074.7 1936.44  5095.7 1940.49  5116.7 1943.22
  5139.3 1944.58  5152.8 1946.46  5167.8 1947.50  5172.3 1948.55  5175.3 1948.55
#Mann=3,-1,0
  4534.1    0.05       0  5029.0    0.05       0  5033.1    0.05       0
Bank Sta=5029,5033.1
Exp/Cntr=0.3,0.1

Type RM Length L Ch R = 1,2840,403,403,403
BEGIN DESCRIPTION:
Deadman 68 6.0
END DESCRIPTION:
XS GIS Cut Line= 3
      1647854.98      6842638.01      1647455.00      6842838.00
      1647405.01      6843137.97
#Sta/Elev= 30
  4553.0 1952.64  4555.8 1952.64  4561.4 1951.30  4567.0 1951.48  4606.1 1947.85
  4628.4 1946.42  4656.4 1945.36  4687.1 1942.69  4723.5 1941.28  4798.9 1935.87
  4821.3 1935.01  4852.1 1932.84  4902.4 1930.59  4924.7 1928.90  4941.5 1928.24
  4947.1 1927.03  4955.5 1926.29  4961.8 1925.01  4962.1 1924.51  4965.7 1924.51
  4965.9 1925.01  4977.8 1925.74  5010.3 1925.75  5033.1 1926.54  5050.9 1926.45
  5132.0 1929.85  5192.8 1933.94  5233.4 1939.44  5284.1 1944.66  5304.3 1946.32
#Mann=3,-1,0
  4553.0    0.05       0  4961.8    0.05       0  4965.9    0.05       0
Bank Sta=4961.8,4965.9
Exp/Cntr=0.3,0.1

Type RM Length L Ch R = 1,2437,262,262,262
BEGIN DESCRIPTION:
Deadman 68 5.0
END DESCRIPTION:
XS GIS Cut Line= 3
      1647088.10      6842292.37      1647106.47      6842684.44
      1647255.00      6843038.01
#Sta/Elev= 30
  4607.5 1957.84  4613.1 1956.37  4623.1 1955.05  4648.1 1952.62  4653.2 1951.00
  4673.2 1947.88  4723.3 1941.51  4733.3 1938.83  4753.3 1935.40  4833.4 1926.25
  4860.1 1924.36  4883.4 1924.20  4913.5 1922.68  4973.5 1921.47  4983.5 1920.38
  5012.6 1920.32  5012.9 1919.82  5016.6 1919.82  5016.8 1920.32  5033.0 1922.78
  5079.8 1924.67  5085.9 1925.76  5091.3 1925.56  5109.6 1927.79  5144.9 1929.95
  5191.8 1931.00  5220.9 1932.47  5275.0 1932.79  5345.1 1934.21  5383.5 1936.17
#Mann=3,-1,0
  4607.5    0.05       0  5012.6    0.05       0  5016.8    0.05       0
Bank Sta=5012.6,5016.8
Exp/Cntr=0.3,0.1

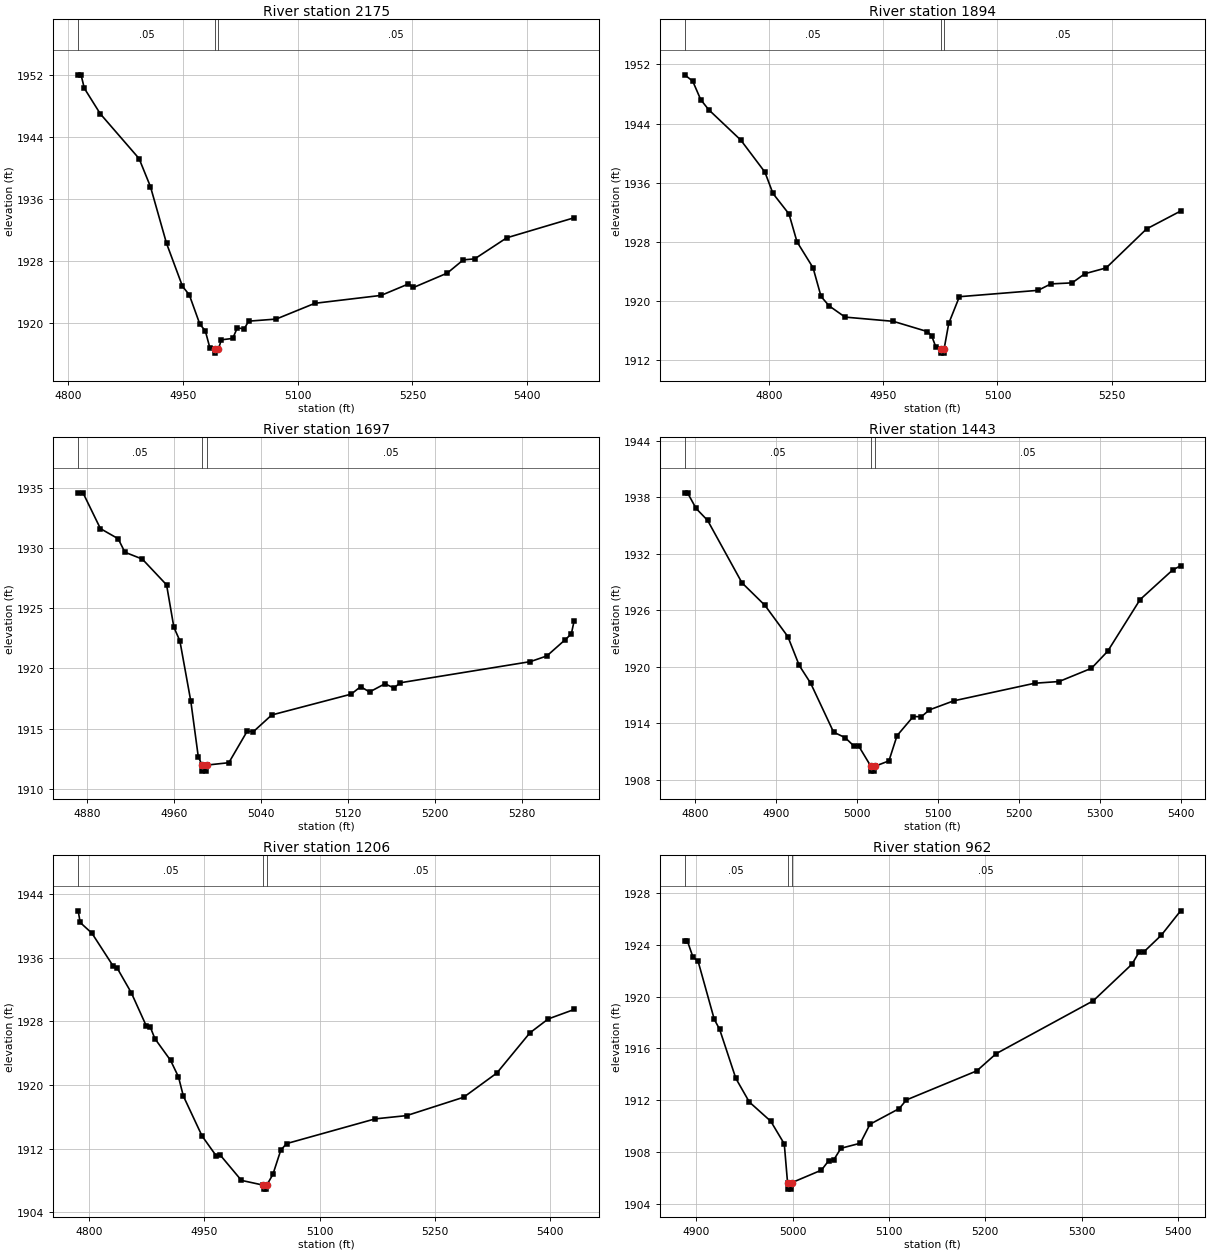
Type RM Length L Ch R = 1,2175,281,281,281
BEGIN DESCRIPTION:
Mapping XS f3d08b77
END DESCRIPTION:
XS GIS Cut Line= 2
      1646795.20      6842486.86      1647163.11      6843021.14
#Sta/Elev= 30
  4812.9 1952.04  4816.6 1952.04  4820.9 1950.30  4841.8 1947.00  4892.5 1941.22
  4907.4 1937.59  4928.4 1930.27  4949.3 1924.71  4958.2 1923.61  4972.1 1919.79
  4979.1 1918.98  4985.2 1916.72  4991.9 1916.58  4992.2 1916.08  4996.2 1916.58
  5000.1 1917.80  5015.0 1917.98  5021.0 1919.35  5029.9 1919.21  5035.9 1920.21
  5071.8 1920.48  5122.5 1922.52  5209.1 1923.54  5244.9 1925.02  5251.4 1924.56
  5295.6 1926.42  5316.6 1928.13  5331.5 1928.26  5373.4 1930.98  5461.6 1933.57
#Mann=3,-1,0
  4812.9    0.05       0  4991.9    0.05       0  4996.2    0.05       0
Bank Sta=4991.9,4996.2
Exp/Cntr=0.3,0.1

Type RM Length L Ch R = 1,1894,197,197,197
BEGIN DESCRIPTION:
Deadman 68 4.0
END DESCRIPTION:
XS GIS Cut Line= 3
      1646704.99      6842587.98      1646805.00      6842888.00
      1647105.03      6843038.02
#Sta/Elev= 30
  4689.0 1950.59  4699.6 1949.73  4710.1 1947.23  4720.6 1945.87  4762.8 1941.76
  4794.4 1937.44  4805.0 1934.55  4826.1 1931.77  4836.6 1928.01  4857.7 1924.50
  4868.2 1920.62  4878.8 1919.35  4899.8 1917.83  4963.1 1917.26  5008.0 1915.87
  5013.6 1915.29  5019.2 1913.74  5025.5 1913.46  5025.8 1912.96  5029.5 1912.96
  5029.8 1913.46  5036.0 1916.98  5050.0 1920.59  5153.4 1921.45  5170.2 1922.32
  5198.1 1922.46  5214.9 1923.70  5242.8 1924.48  5295.9 1929.75  5340.7 1932.17
#Mann=3,-1,0
  4689.0    0.05       0  5025.5    0.05       0  5029.8    0.05       0
Bank Sta=5025.5,5029.8
Exp/Cntr=0.3,0.1

Type RM Length L Ch R = 1,1697,254,254,254
BEGIN DESCRIPTION:
Mapping XS 8e4d2a88
END DESCRIPTION:
XS GIS Cut Line= 2
      1646542.10      6842943.78      1646951.08      6843144.77
#Sta/Elev= 30
  4872.2 1934.58  4876.6 1934.58  4892.6 1931.61  4908.9 1930.77  4915.1 1929.65
  4931.1 1929.08  4953.4 1926.94  4960.1 1923.42  4965.6 1922.30  4975.7 1917.26
  4982.5 1912.69  4986.0 1911.98  4986.3 1911.48  4990.0 1911.48  4990.3 1911.98
  5010.6 1912.18  5027.5 1914.80  5033.1 1914.75  5050.0 1916.14  5123.0 1917.87
  5131.7 1918.49  5139.9 1918.05  5154.0 1918.73  5162.4 1918.38  5167.9 1918.81
  5287.7 1920.57  5302.8 1921.04  5319.7 1922.39  5325.3 1922.87  5327.9 1923.96
#Mann=3,-1,0
  4872.2    0.05       0  4986.0    0.05       0  4990.3    0.05       0
Bank Sta=4986,4990.3
Exp/Cntr=0.3,0.1

Type RM Length L Ch R = 1,1443,237,237,237
BEGIN DESCRIPTION:
Deadman 68 3.0
END DESCRIPTION:
XS GIS Cut Line= 3
      1646455.01      6843088.01      1646605.00      6843238.00
      1647004.99      6843238.00
#Sta/Elev= 30
  4787.4 1938.49  4790.9 1938.49  4801.5 1936.83  4815.7 1935.56  4858.1 1928.93
  4886.4 1926.54  4914.7 1923.22  4928.8 1920.15  4942.9 1918.26  4971.2 1913.06
  4985.4 1912.48  4996.0 1911.61  5002.0 1911.61  5017.3 1909.42  5017.6 1908.92
  5021.4 1908.92  5021.7 1909.42  5039.5 1910.01  5049.5 1912.69  5069.5 1914.72
  5079.5 1914.70  5089.5 1915.43  5119.5 1916.39  5219.5 1918.26  5249.5 1918.44
  5289.5 1919.85  5309.5 1921.66  5349.5 1927.15  5389.5 1930.28  5399.5 1930.74
#Mann=3,-1,0
  4787.4    0.05       0  5017.3    0.05       0  5021.7    0.05       0
Bank Sta=5017.3,5021.7
Exp/Cntr=0.3,0.1

Type RM Length L Ch R = 1,1206,244,244,244
BEGIN DESCRIPTION:
Mapping XS f0cda819
END DESCRIPTION:
XS GIS Cut Line= 2
      1646347.56      6843412.44      1646977.95      6843555.39
#Sta/Elev= 30
  4785.5 1941.88  4788.0 1940.42  4803.4 1939.06  4831.1 1934.93  4836.3 1934.68
  4854.7 1931.58  4874.3 1927.40  4879.4 1927.28  4885.4 1925.82  4905.9 1923.08
  4916.2 1921.00  4922.5 1918.61  4946.9 1913.58  4965.6 1911.05  4970.7 1911.17
  4998.2 1908.00  5026.8 1907.40  5027.1 1906.90  5030.9 1906.90  5031.2 1907.40
  5039.2 1908.74  5049.5 1911.79  5057.0 1912.62  5172.5 1915.73  5213.5 1916.14
  5287.9 1918.45  5331.1 1921.49  5374.2 1926.54  5398.1 1928.29  5431.9 1929.48
#Mann=3,-1,0
  4785.5    0.05       0  5026.8    0.05       0  5031.2    0.05       0
Bank Sta=5026.8,5031.2
Exp/Cntr=0.3,0.1

Type RM Length L Ch R = 1,962,450,450,450
BEGIN DESCRIPTION:
Deadman 68 2.0
END DESCRIPTION:
XS GIS Cut Line= 3
      1646405.00      6843638.00      1646505.00      6843688.00
      1646904.98      6843738.00
#Sta/Elev= 30
  4888.0 1924.32  4890.8 1924.32  4896.4 1923.11  4902.0 1922.73  4918.7 1918.26
  4924.3 1917.48  4941.1 1913.69  4955.1 1911.86  4977.4 1910.37  4991.4 1908.62
  4994.8 1905.62  4995.1 1905.12  4998.9 1905.12  4999.2 1905.62  5030.0 1906.59
  5037.6 1907.33  5042.6 1907.36  5050.2 1908.28  5070.3 1908.67  5080.4 1910.14
  5110.7 1911.35  5118.2 1912.02  5191.3 1914.27  5211.4 1915.60  5312.2 1919.69
  5352.5 1922.53  5360.1 1923.50  5365.1 1923.50  5382.8 1924.76  5402.9 1926.65
#Mann=3,-1,0
  4888.0    0.05       0  4994.8    0.05       0  4999.2    0.05       0
Bank Sta=4994.8,4999.2
Exp/Cntr=0.3,0.1

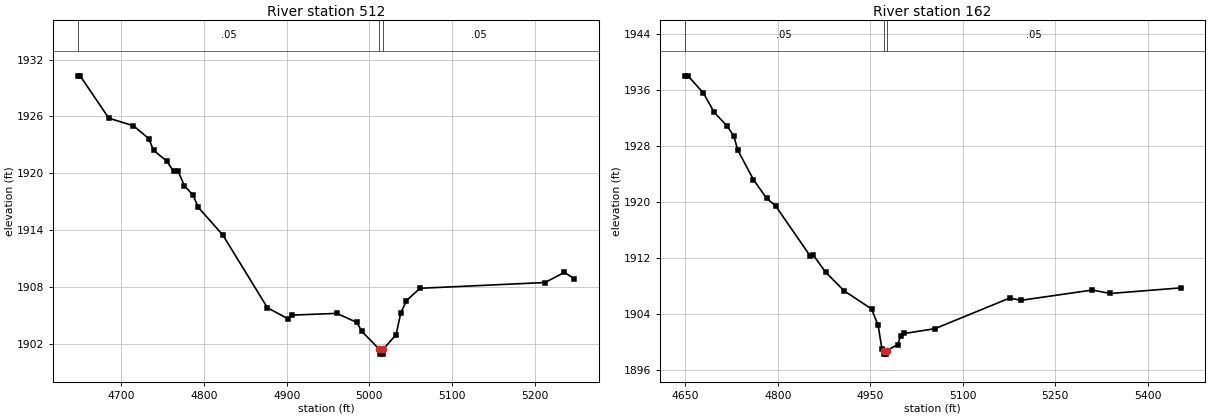
Type RM Length L Ch R = 1,512,350,350,350
BEGIN DESCRIPTION:
Mapping XS b3dfca2c
END DESCRIPTION:
XS GIS Cut Line= 3
      1646216.38      6843768.64      1646340.58      6844082.65
      1646580.96      6844187.67
#Sta/Elev= 30
  4647.8 1930.28  4650.1 1930.28  4684.8 1925.81  4714.5 1925.01  4733.1 1923.66
  4738.9 1922.42  4754.7 1921.30  4763.2 1920.19  4768.6 1920.21  4776.2 1918.69
  4786.9 1917.66  4792.9 1916.41  4822.7 1913.48  4876.7 1905.80  4901.1 1904.65
  4906.5 1905.02  4960.5 1905.20  4984.7 1904.26  4991.1 1903.29  5012.2 1901.40
  5012.6 1900.90  5016.4 1900.90  5016.7 1901.40  5032.4 1902.96  5037.9 1905.21
  5044.9 1906.55  5061.3 1907.85  5212.6 1908.46  5236.0 1909.53  5247.8 1908.88
#Mann=3,-1,0
  4647.8    0.05       0  5012.2    0.05       0  5016.7    0.05       0
Bank Sta=5012.2,5016.7
Exp/Cntr=0.3,0.1

Type RM Length L Ch R = 1,162,0,0,0
BEGIN DESCRIPTION:
Deadman 68 1.0
END DESCRIPTION:
XS GIS Cut Line= 3
      1645980.01      6843763.02      1646100.29      6844093.09
      1646524.74      6844253.35
#Sta/Elev= 30
  4648.7 1938.06  4654.0 1938.06  4679.2 1935.59  4696.6 1932.85  4717.9 1930.86
  4728.5 1929.43  4735.1 1927.40  4760.3 1923.25  4781.7 1920.56  4796.2 1919.50
  4852.0 1912.39  4857.3 1912.49  4877.3 1910.03  4907.8 1907.34  4952.0 1904.77
  4962.7 1902.44  4969.0 1899.00  4972.0 1898.82  4972.3 1898.32  4976.2 1898.32
  4976.5 1898.82  4994.2 1899.67  4999.5 1900.93  5005.2 1901.27  5054.8 1901.95
  5176.1 1906.32  5195.0 1906.01  5310.4 1907.47  5339.5 1906.98  5453.7 1907.78
#Mann=3,-1,0
  4648.7    0.05       0  4972.0    0.05       0  4976.5    0.05       0
Bank Sta=4972,4976.5
Exp/Cntr=0.3,0.1

Chan Stop Cuts=-1