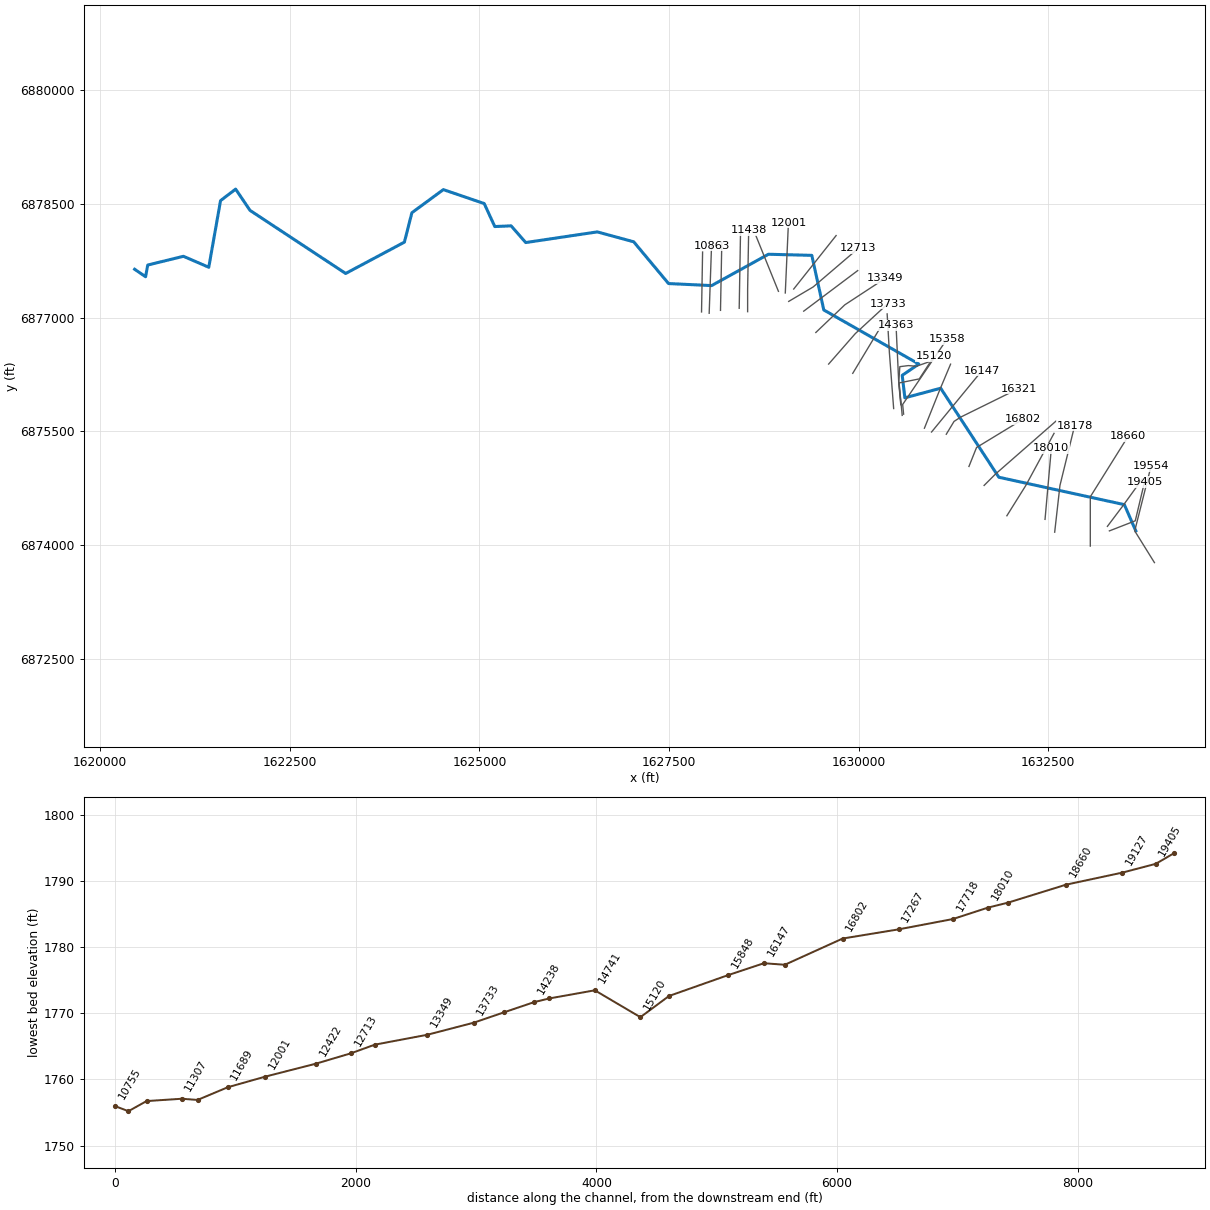
--- Deadman 70.prj (project) ---

Proj Title=Deadman 70 Base Level Engineering
Current Plan=p01
Default Exp/Contr=0.3,0.1
English Units
Geom File=g01
Flow File=f01
Plan File=p01
Y Axis Title=Elevation
X Axis Title(PF)=Main Channel Distance
X Axis Title(XS)=Station
BEGIN DESCRIPTION:
Deadman 70
END DESCRIPTION:
DSS Export Rating Curves= 0
DSS Export Rating Curve Sorted= 0
DSS Export Volume Flow Curves= 0
DXF OffsetX= 0
DXF OffsetY= 0
DXF ScaleX= 1
DXF ScaleY= 10

--- Deadman 70.p01 (plan) ---

Plan Title=Multiple Run
Short Identifier=Multiple
Geom File=g01
Flow File=f01
Subcritical Flow
K Sum by GR= 0
Std Step Tol= 0.01
Critical Tol= 0.01
Num of Std Step Trials= 20
Max Error Tol= 0.3
Flow Tol Ratio= 0.001
Split Flow NTrial= 30
Split Flow Tol= 0.02
Split Flow Ratio= 0.02
Log Output Level= 0
Friction Slope Method= 1
Unsteady Friction Slope Method= 2
Unsteady Bridges Friction Slope Method= 1
Parabolic Critical Depth
Global Vel Dist=  1 , 1 , 1
Global Log Level= 0
CheckData=True
Encroach Param= -1, 0, 0, 0
BEGIN DESCRIPTION:
Multiple Run
END DESCRIPTION:

--- Deadman 70.f01 (steady flow) ---

Flow Title=Multiple
Number of Profiles=7
Profile Names=10-year,25-year,50-year,1pct_min,100-year,1pct_plu,500-year
River Rch & RM= Deadman 70,Reach-1,19554
     267     368     451     275     549    1095     825
River Rch & RM= Deadman 70,Reach-1,19405
     332     463     571     351     700    1396    1064
River Rch & RM= Deadman 70,Reach-1,10273
     441     624     778     482     962    1920    1490
River Rch & RM= Deadman 70,Reach-1,6530
     479     683     856     532    1062    2120    1660
River Rch & RM= Deadman 70,Reach-1,1235
     648     937    1184     743    1483    2959    2358
Boundary for River Rch & Prof#=Deadman 70,Reach-1,1
Up Type=0
Dn Type=3
Dn Slope=0.007
Boundary for River Rch & Prof#=Deadman 70,Reach-1,2
Up Type=0
Dn Type=3
Dn Slope=0.007
Boundary for River Rch & Prof#=Deadman 70,Reach-1,3
Up Type=0
Dn Type=3
Dn Slope=0.007
Boundary for River Rch & Prof#=Deadman 70,Reach-1,4
Up Type=0
Dn Type=3
Dn Slope=0.007
Boundary for River Rch & Prof#=Deadman 70,Reach-1,5
Up Type=0
Dn Type=3
Dn Slope=0.007
Boundary for River Rch & Prof#=Deadman 70,Reach-1,6
Up Type=0
Dn Type=3
Dn Slope=0.007
Boundary for River Rch & Prof#=Deadman 70,Reach-1,7
Up Type=0
Dn Type=3
Dn Slope=0.007

--- Deadman 70.g01 (geometry) ---

Geom Title=Existing Conditions

River Reach=Deadman 70,Reach-1
Reach XY= 30
      1633655.00      6874188.00      1633503.78      6874534.57
      1631848.81      6874895.82      1631082.26      6876069.32
      1630610.08      6875943.03      1630574.95      6876239.47
      1630793.94      6876388.36      1629541.19      6877101.23
      1629383.08      6877821.28      1628810.93      6877835.76
      1628062.02      6877422.67      1627494.05      6877449.46
      1627034.79      6878000.09      1626554.90      6878130.66
      1625610.85      6877990.06      1625418.32      6878210.42
      1625203.24      6878201.05      1625063.76      6878504.27
      1624524.99      6878688.06      1624110.26      6878383.34
      1624011.38      6877995.36      1623237.13      6877582.47
      1621975.71      6878414.52      1621786.50      6878694.70
      1621587.58      6878543.09      1621432.17      6877664.42
      1621098.36      6877808.84      1620627.39      6877693.70
      1620599.14      6877539.49      1620455.00      6877638.00

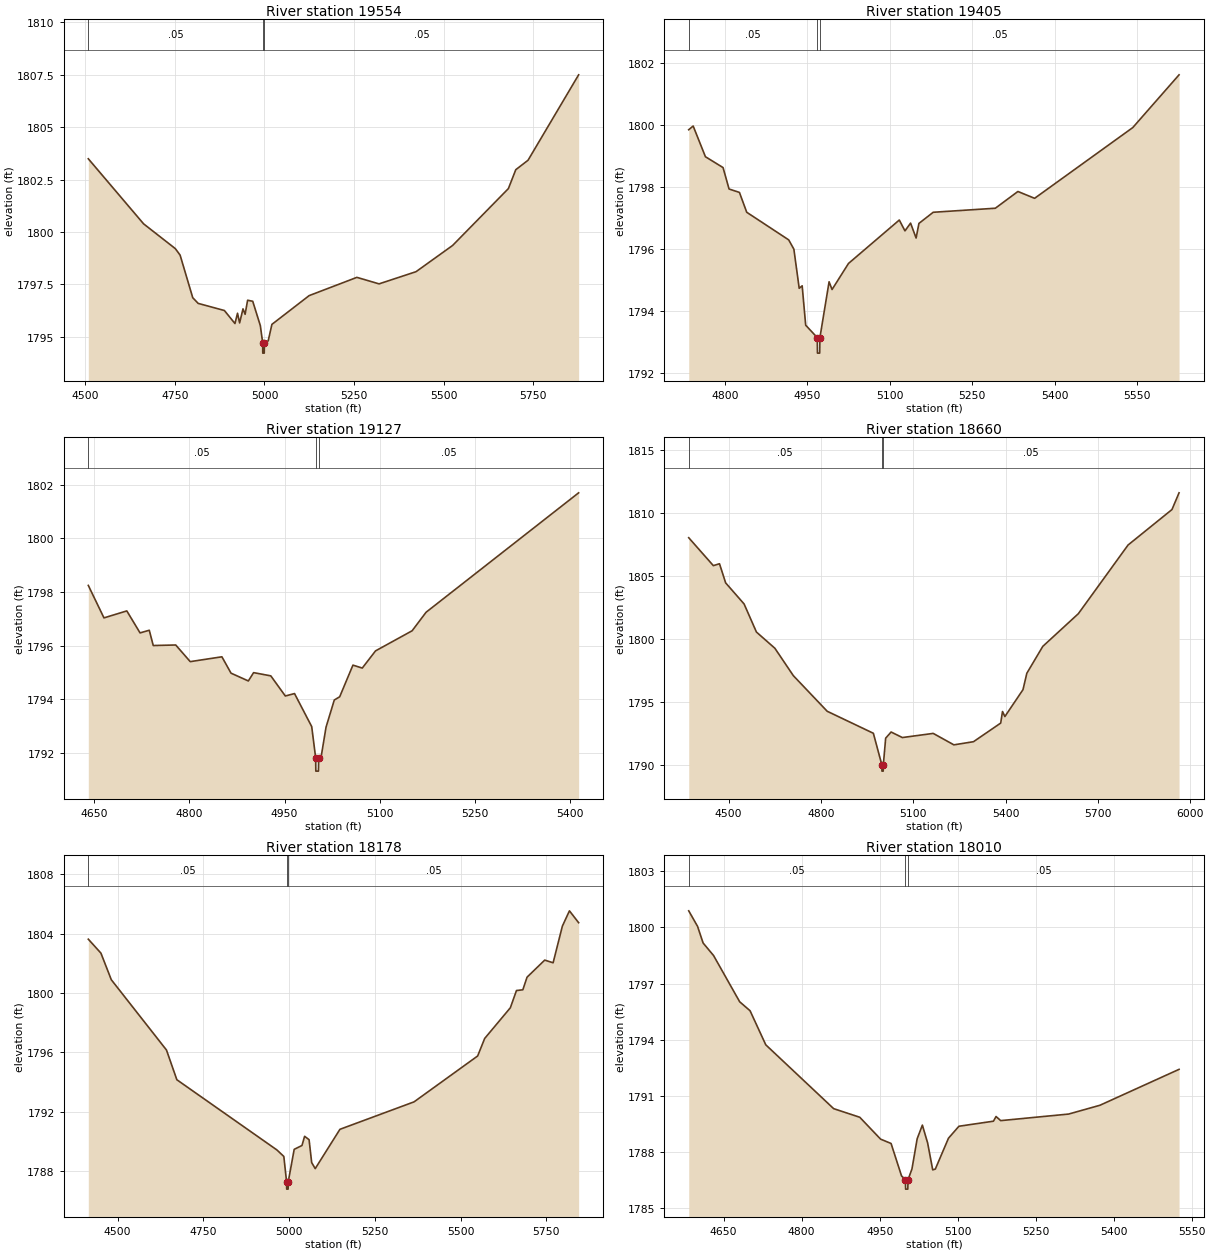
Type RM Length L Ch R = 1,19554,149,149,149
BEGIN DESCRIPTION:
Deadman 70 32.0
END DESCRIPTION:
XS GIS Cut Line= 3
      1633900.43      6873770.39      1633640.67      6874188.38
      1633855.01      6875038.03
#Sta/Elev= 30
  4508.4 1803.49  4662.7 1800.39  4751.2 1799.21  4764.6 1798.90  4799.9 1796.87
  4815.0 1796.60  4888.2 1796.26  4917.7 1795.64  4924.8 1796.13  4930.7 1795.67
  4940.1 1796.34  4946.0 1796.08  4953.0 1796.75  4967.3 1796.70  4988.5 1795.54
  4995.0 1794.73  4995.3 1794.23  4999.4 1794.23  4999.8 1794.73  5010.4 1794.81
  5020.8 1795.60  5124.7 1796.97  5258.0 1797.84  5319.8 1797.53  5423.0 1798.11
  5525.1 1799.36  5680.8 1802.07  5701.4 1802.97  5735.6 1803.42  5876.8 1807.49
#Mann=3,-1,0
  4508.4    0.05       0  4995.0    0.05       0  4999.8    0.05       0
Bank Sta=4995,4999.8
Exp/Cntr=0.3,0.1

Type RM Length L Ch R = 1,19405,278,278,278
BEGIN DESCRIPTION:
Mapping XS cc73e5a2
END DESCRIPTION:
XS GIS Cut Line= 3
      1633306.63      6874188.46      1633647.77      6874321.27
      1633769.94      6874833.31
#Sta/Elev= 30
  4734.0 1799.85  4742.1 1799.97  4764.4 1798.98  4796.5 1798.63  4807.4 1797.94
  4826.3 1797.83  4839.6 1797.19  4916.0 1796.30  4925.4 1796.00  4935.1 1794.74
  4940.5 1794.82  4946.9 1793.55  4968.0 1793.15  4968.3 1792.65  4972.4 1792.65
  4972.8 1793.15  4989.5 1794.95  4994.9 1794.70  5024.8 1795.54  5117.3 1796.94
  5127.6 1796.59  5137.8 1796.84  5147.9 1796.36  5153.0 1796.83  5179.0 1797.19
  5292.1 1797.32  5333.2 1797.86  5363.6 1797.64  5542.3 1799.92  5626.5 1801.62
#Mann=3,-1,0
  4734.0    0.05       0  4968.0    0.05       0  4972.8    0.05       0
Bank Sta=4968,4972.8
Exp/Cntr=0.3,0.1

Type RM Length L Ch R = 1,19127,467,467,467
BEGIN DESCRIPTION:
Mapping XS e1e4ac79
END DESCRIPTION:
XS GIS Cut Line= 3
      1633280.55      6874248.31      1633483.74      6874517.82
      1633738.90      6874870.72
#Sta/Elev= 30
  4640.6 1798.24  4665.3 1797.03  4701.3 1797.29  4722.2 1796.47  4736.7 1796.57
  4743.0 1796.00  4778.4 1796.02  4801.3 1795.40  4851.2 1795.58  4865.6 1794.97
  4892.9 1794.68  4901.2 1794.99  4928.3 1794.87  4951.2 1794.12  4965.7 1794.21
  4992.8 1792.98  4999.0 1791.82  4999.3 1791.32  5003.4 1791.32  5003.8 1791.82
  5007.5 1791.83  5015.4 1792.96  5028.4 1793.97  5036.9 1794.09  5057.8 1795.27
  5072.5 1795.16  5093.4 1795.80  5151.1 1796.55  5173.1 1797.24  5413.6 1801.69
#Mann=3,-1,0
  4640.6    0.05       0  4999.0    0.05       0  5003.8    0.05       0
Bank Sta=4999,5003.8
Exp/Cntr=0.3,0.1

Type RM Length L Ch R = 1,18660,482,482,482
BEGIN DESCRIPTION:
Deadman 70 31.0
END DESCRIPTION:
XS GIS Cut Line= 3
      1633055.00      6873988.00      1633055.00      6874638.00
      1633555.00      6875438.00
#Sta/Elev= 30
  4370.3 1808.06  4450.3 1805.84  4470.3 1805.99  4490.3 1804.47  4550.3 1802.79
  4590.3 1800.56  4650.3 1799.27  4710.3 1797.09  4820.3 1794.26  4970.3 1792.51
  4997.9 1790.00  4998.2 1789.50  5002.3 1789.50  5002.7 1790.00  5010.3 1792.12
  5028.0 1792.61  5064.5 1792.17  5164.8 1792.50  5232.0 1791.59  5295.7 1791.84
  5384.1 1793.32  5390.0 1794.24  5397.7 1793.84  5456.6 1795.98  5469.0 1797.28
  5520.9 1799.42  5636.5 1802.02  5798.0 1807.48  5940.7 1810.30  5963.7 1811.63
#Mann=3,-1,0
  4370.3    0.05       0  4997.9    0.03       0  5002.7    0.05       0
Bank Sta=4997.9,5002.7
Exp/Cntr=0.3,0.1

Type RM Length L Ch R = 1,18178,168,168,168
BEGIN DESCRIPTION:
Deadman 70 30.0
END DESCRIPTION:
XS GIS Cut Line= 3
      1632585.30      6874171.44      1632655.00      6874788.00
      1632848.06      6875574.05
#Sta/Elev= 30
  4414.4 1803.62  4451.2 1802.68  4481.4 1800.89  4642.4 1796.15  4672.6 1794.15
  4964.4 1789.42  4984.6 1788.98  4992.6 1787.28  4992.9 1786.78  4997.1 1786.78
  4997.5 1787.28  5014.8 1789.46  5037.5 1789.72  5045.2 1790.34  5058.2 1790.11
  5065.8 1788.57  5076.1 1788.16  5148.2 1790.81  5364.4 1792.66  5549.8 1795.75
  5570.3 1796.93  5645.2 1799.00  5663.0 1800.16  5681.6 1800.21  5693.9 1801.06
  5745.4 1802.21  5769.9 1802.03  5796.9 1804.50  5817.5 1805.53  5844.3 1804.73
#Mann=3,-1,0
  4414.4    0.05       0  4992.6    0.05       0  4997.5    0.05       0
Bank Sta=4992.6,4997.5
Exp/Cntr=0.3,0.1

Type RM Length L Ch R = 1,18010,292,292,292
BEGIN DESCRIPTION:
Mapping XS 5a6616b2
END DESCRIPTION:
XS GIS Cut Line= 2
      1632458.11      6874340.41      1632541.44      6875279.63
#Sta/Elev= 30
  4582.9 1800.89  4599.9 1800.06  4610.6 1799.17  4630.7 1798.50  4680.9 1796.03
  4700.9 1795.55  4731.1 1793.73  4861.6 1790.32  4911.8 1789.86  4951.9 1788.69
  4972.0 1788.46  4992.1 1786.73  4999.6 1786.52  5000.0 1786.02  5004.2 1786.02
  5004.6 1786.52  5012.2 1787.10  5022.2 1788.71  5032.2 1789.44  5042.3 1788.49
  5052.1 1787.05  5057.1 1787.09  5082.4 1788.74  5102.5 1789.38  5168.9 1789.65
  5173.9 1789.90  5182.8 1789.68  5313.3 1790.03  5373.6 1790.50  5525.8 1792.42
#Mann=3,-1,0
  4582.9    0.05       0  4999.6    0.05       0  5004.6    0.05       0
Bank Sta=4999.6,5004.6
Exp/Cntr=0.3,0.1

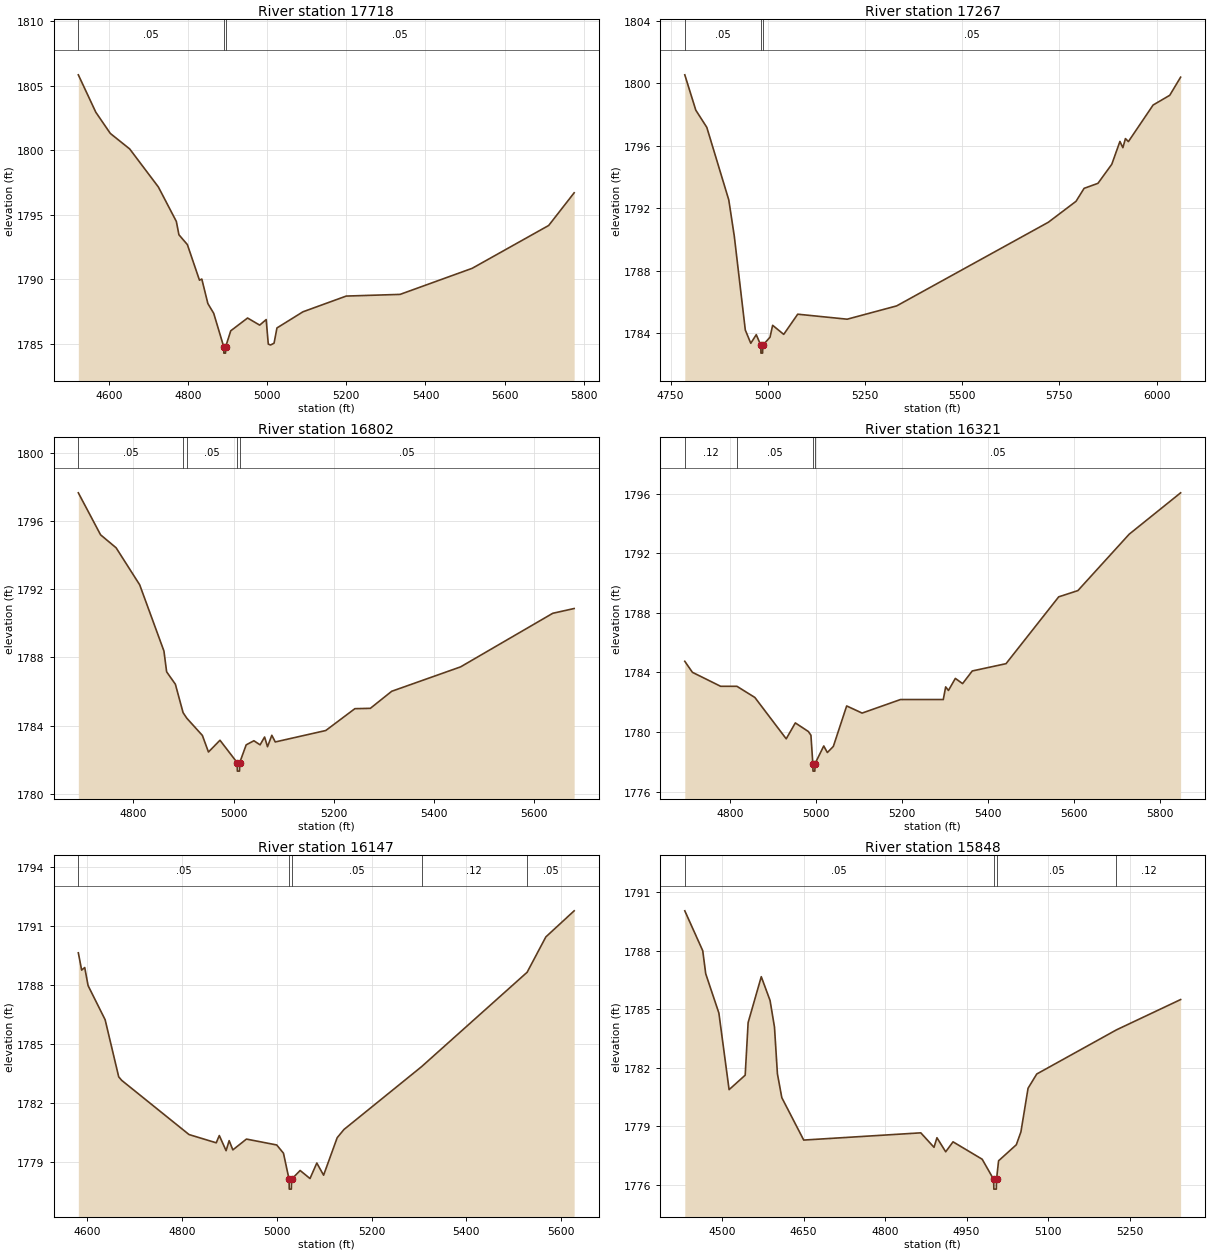
Type RM Length L Ch R = 1,17718,451,451,451
BEGIN DESCRIPTION:
Deadman 70 29.0
END DESCRIPTION:
XS GIS Cut Line= 3
      1631955.00      6874388.00      1632205.00      6874788.00
      1632576.63      6875474.57
#Sta/Elev= 30
  4523.1 1805.85  4567.3 1802.95  4603.9 1801.31  4652.8 1800.11  4725.3 1797.16
  4770.7 1794.49  4777.2 1793.46  4798.5 1792.70  4829.1 1789.94  4835.0 1790.03
  4850.3 1788.13  4865.1 1787.37  4890.3 1784.79  4890.7 1784.29  4894.9 1784.29
  4895.3 1784.79  4908.1 1786.02  4950.6 1787.01  4981.2 1786.46  4997.6 1786.89
  5002.9 1784.99  5008.6 1784.92  5017.5 1785.06  5024.8 1786.24  5090.4 1787.49
  5199.8 1788.71  5335.8 1788.84  5517.9 1790.86  5711.2 1794.18  5775.5 1796.71
#Mann=3,-1,0
  4523.1    0.05       0  4890.3    0.05       0  4895.3    0.05       0
Bank Sta=4890.3,4895.3
Exp/Cntr=0.3,0.1

Type RM Length L Ch R = 1,17267,465,465,465
BEGIN DESCRIPTION:
Deadman 70 28.0
END DESCRIPTION:
XS GIS Cut Line= 3
      1631655.00      6874788.00      1631805.00      6874938.00
      1632604.97      6875637.97
#Sta/Elev= 30
  4786.7 1800.53  4815.0 1798.27  4843.3 1797.17  4899.8 1792.53  4914.0 1790.21
  4942.3 1784.21  4956.4 1783.36  4970.5 1783.91  4982.2 1783.23  4982.5 1782.73
  4986.8 1782.73  4987.2 1783.23  5005.9 1783.75  5012.6 1784.51  5041.1 1783.93
  5077.1 1785.22  5204.3 1784.90  5331.5 1785.75  5721.6 1791.10  5792.8 1792.44
  5813.6 1793.27  5849.2 1793.59  5884.8 1794.81  5905.7 1796.27  5913.3 1795.87
  5919.9 1796.45  5927.5 1796.26  5991.1 1798.60  6033.8 1799.22  6061.8 1800.38
#Mann=3,-1,0
  4786.7    0.05       0  4982.2    0.05       0  4987.2    0.05       0
Bank Sta=4982.2,4987.2
Exp/Cntr=0.3,0.1

Type RM Length L Ch R = 1,16802,481,481,481
BEGIN DESCRIPTION:
Deadman 70 27.0
END DESCRIPTION:
XS GIS Cut Line= 3
      1631455.01      6875038.03      1631555.00      6875288.00
      1632170.63      6875662.67
#Sta/Elev= 30
  4690.1 1797.65  4734.5 1795.19  4765.5 1794.43  4812.6 1792.26  4861.0 1788.38
  4866.4 1787.16  4883.9 1786.43  4899.2 1784.77  4906.7 1784.44  4937.8 1783.43
  4949.9 1782.46  4972.9 1783.15  5007.2 1781.84  5007.6 1781.34  5011.9 1781.34
  5012.3 1781.84  5025.2 1782.88  5040.6 1783.12  5053.0 1782.88  5062.0 1783.34
  5067.8 1782.77  5076.4 1783.44  5083.3 1783.05  5184.1 1783.72  5242.2 1785.00
  5273.1 1785.02  5315.8 1786.02  5453.3 1787.45  5637.3 1790.59  5680.0 1790.87
#Mann=5,-1,0
  4690.1    0.05       0  4899.2    0.12       0  4906.7    0.05       0
  5007.2    0.05       0  5012.3    0.05       0
Bank Sta=5007.2,5012.3
Exp/Cntr=0.3,0.1

Type RM Length L Ch R = 1,16321,174,174,174
BEGIN DESCRIPTION:
Mapping XS c5563477
END DESCRIPTION:
XS GIS Cut Line= 4
      1631156.17      6875462.85      1631258.59      6875632.16
      1631349.54      6875690.45      1632109.31      6876064.83
#Sta/Elev= 30
  4694.1 1784.75  4711.8 1784.01  4777.4 1783.07  4815.3 1783.07  4857.0 1782.32
  4929.9 1779.54  4951.1 1780.61  4981.5 1780.03  4987.4 1779.78  4991.8 1777.87
  4992.2 1777.37  4996.5 1777.37  4996.9 1777.87  5017.2 1779.06  5025.6 1778.62
  5039.5 1779.03  5070.5 1781.75  5106.4 1781.27  5195.6 1782.18  5295.1 1782.18
  5300.7 1783.03  5307.1 1782.79  5323.2 1783.60  5340.0 1783.25  5362.5 1784.10
  5441.0 1784.59  5563.5 1789.08  5608.1 1789.50  5727.4 1793.29  5847.0 1796.07
#Mann=4,-1,0
  4694.1    0.12       0  4815.3    0.05       0  4991.8    0.05       0
  4996.9    0.05       0
Bank Sta=4991.8,4996.9
Exp/Cntr=0.3,0.1

Type RM Length L Ch R = 1,16147,299,299,299
BEGIN DESCRIPTION:
Mapping XS b20aefc2
END DESCRIPTION:
XS GIS Cut Line= 2
      1630961.78      6875492.11      1631626.49      6876301.05
#Sta/Elev= 30
  4580.7 1789.64  4587.7 1788.76  4594.2 1788.89  4601.3 1787.97  4637.3 1786.23
  4666.0 1783.32  4672.4 1783.14  4814.5 1780.38  4871.9 1779.96  4878.4 1780.33
  4892.7 1779.56  4899.2 1780.07  4907.0 1779.60  4935.7 1780.15  4999.6 1779.85
  5013.9 1779.43  5025.7 1778.10  5026.1 1777.60  5030.5 1777.60  5030.9 1778.10
  5049.1 1778.55  5069.9 1778.14  5084.3 1778.93  5098.6 1778.31  5127.3 1780.22
  5141.7 1780.64  5305.5 1783.84  5528.4 1788.65  5567.9 1790.45  5627.7 1791.78
#Mann=5,-1,0
  4580.7    0.05       0  5025.7    0.03       0  5030.9    0.05       0
  5305.5    0.12       0  5528.4    0.05       0
Bank Sta=5025.7,5030.9
Exp/Cntr=0.3,0.1

Type RM Length L Ch R = 1,15848,490,490,490
BEGIN DESCRIPTION:
Mapping XS 245b726a
END DESCRIPTION:
XS GIS Cut Line= 3
      1630867.74      6875542.29      1631064.21      6876033.47
      1631212.62      6876386.75
#Sta/Elev= 30
  4431.6 1790.03  4464.6 1787.99  4470.1 1786.81  4494.3 1784.80  4513.1 1780.88
  4542.7 1781.62  4548.1 1784.31  4572.3 1786.66  4588.5 1785.44  4596.6 1784.08
  4602.0 1781.69  4610.1 1780.47  4650.4 1778.30  4865.8 1778.67  4890.1 1777.93
  4895.5 1778.42  4911.6 1777.70  4925.1 1778.21  4978.7 1777.32  4999.8 1776.29
  5000.2 1775.79  5004.7 1775.79  5005.1 1776.29  5008.9 1777.24  5041.5 1778.06
  5050.0 1778.72  5063.1 1780.95  5079.1 1781.68  5225.8 1783.94  5343.8 1785.49
#Mann=4,-1,0
  4431.6    0.05       0  4999.8    0.03       0  5005.1    0.05       0
  5225.8    0.12       0
Bank Sta=4999.8,5005.1
Exp/Cntr=0.3,0.1

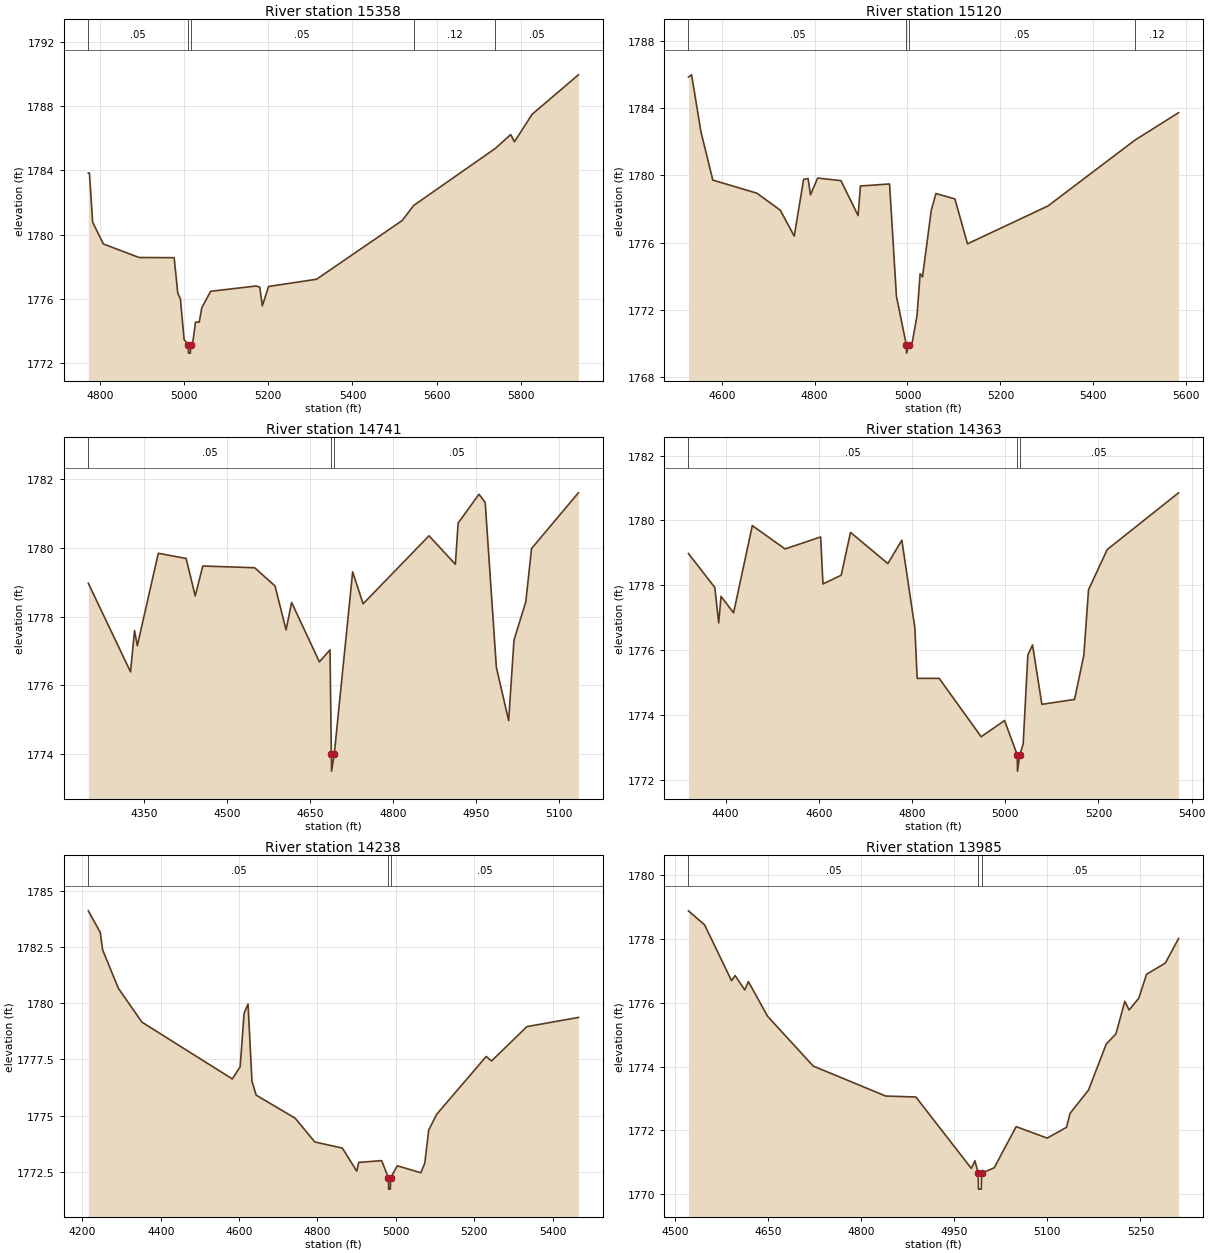
Type RM Length L Ch R = 1,15358,238,238,238
BEGIN DESCRIPTION:
Mapping XS 62d758af
END DESCRIPTION:
XS GIS Cut Line= 3
      1630593.53      6875727.70      1630581.07      6875855.25
      1631162.46      6876712.79
#Sta/Elev= 30
  4772.5 1783.83  4775.2 1783.83  4782.9 1780.77  4808.4 1779.42  4893.4 1778.58
  4976.5 1778.57  4985.2 1776.34  4991.2 1776.03  5000.1 1773.49  5010.1 1773.14
  5010.5 1772.64  5015.0 1772.64  5015.4 1773.14  5021.1 1773.38  5027.2 1774.56
  5036.1 1774.57  5042.1 1775.46  5063.1 1776.48  5170.9 1776.81  5179.8 1776.74
  5185.9 1775.58  5200.8 1776.78  5314.8 1777.23  5518.3 1780.88  5545.3 1781.81
  5739.5 1785.36  5775.9 1786.22  5784.8 1785.77  5826.8 1787.48  5936.7 1789.93
#Mann=5,-1,0
  4772.5    0.05       0  5010.1    0.03       0  5015.4    0.05       0
  5545.3    0.12       0  5739.5    0.05       0
Bank Sta=5010.1,5015.4
Exp/Cntr=0.3,0.1

Type RM Length L Ch R = 1,15120,379,379,379
BEGIN DESCRIPTION:
Mapping XS e2460c5f
END DESCRIPTION:
XS GIS Cut Line= 4
      1630575.06      6875711.21      1630534.00      6876139.19
      1630800.24      6876192.44      1630993.75      6876488.55
#Sta/Elev= 30
  4528.4 1785.85  4535.2 1785.98  4555.3 1782.59  4580.9 1779.72  4675.9 1778.94
  4726.1 1777.93  4756.2 1776.39  4776.3 1779.76  4786.1 1779.81  4791.1 1778.84
  4806.5 1779.84  4856.7 1779.69  4893.7 1777.61  4898.7 1779.37  4961.4 1779.49
  4976.2 1772.81  4997.5 1769.93  4997.9 1769.43  5002.8 1769.93  5010.4 1770.09
  5020.6 1771.67  5027.2 1774.15  5032.3 1773.96  5051.2 1777.92  5061.3 1778.92
  5102.1 1778.60  5129.2 1775.93  5302.4 1778.18  5489.4 1782.09  5583.6 1783.73
#Mann=4,-1,0
  4528.4    0.05       0  4997.5    0.03       0  5002.8    0.05       0
  5489.4    0.12       0
Bank Sta=4997.5,5002.8
Exp/Cntr=0.3,0.1

Type RM Length L Ch R = 1,14741,378,378,378
BEGIN DESCRIPTION:
Mapping XS 99f6c637
END DESCRIPTION:
XS GIS Cut Line= 6
      1630557.88      6875861.99      1630530.27      6876161.29
      1630543.63      6876353.68      1630656.74      6876367.93
      1630761.84      6876359.02      1630924.86      6876416.03
#Sta/Elev= 30
  4249.6 1778.97  4325.9 1776.39  4333.2 1777.59  4338.2 1777.15  4376.1 1779.84
  4426.4 1779.69  4442.8 1778.60  4456.5 1779.47  4550.2 1779.42  4587.0 1778.89
  4607.0 1777.61  4617.0 1778.41  4667.2 1776.68  4686.4 1777.03  4688.8 1774.00
  4689.2 1773.50  4694.1 1774.00  4727.3 1779.30  4746.2 1778.37  4865.3 1780.35
  4912.9 1779.52  4917.9 1780.72  4955.6 1781.56  4966.8 1781.32  4987.0 1776.52
  5009.2 1774.97  5018.8 1777.31  5040.2 1778.43  5050.6 1779.98  5135.2 1781.60
#Mann=3,-1,0
  4249.6    0.05       0  4688.8    0.03       0  4694.1    0.05       0
Bank Sta=4688.8,4694.1
Exp/Cntr=0.3,0.1

Type RM Length L Ch R = 1,14363,125,125,125
BEGIN DESCRIPTION:
Mapping XS e8909882
END DESCRIPTION:
XS GIS Cut Line= 3
      1630556.30      6875851.59      1630529.13      6876144.25
      1630493.59      6876900.90
#Sta/Elev= 30
  4320.5 1778.98  4377.1 1777.93  4385.4 1776.84  4390.4 1777.66  4417.3 1777.15
  4457.5 1779.84  4527.8 1779.12  4604.1 1779.49  4609.1 1778.04  4648.2 1778.31
  4668.2 1779.63  4748.3 1778.67  4778.3 1779.39  4806.2 1776.69  4811.2 1775.13
  4858.4 1775.13  4948.5 1773.33  4998.6 1773.83  5025.9 1772.77  5026.4 1772.27
  5031.3 1772.77  5038.6 1773.11  5048.6 1775.85  5058.7 1776.16  5078.7 1774.33
  5148.8 1774.48  5168.8 1775.85  5178.8 1777.86  5218.8 1779.10  5371.9 1780.85
#Mann=3,-1,0
  4320.5    0.05       0  5025.9    0.03       0  5031.3    0.05       0
Bank Sta=5025.9,5031.3
Exp/Cntr=0.3,0.1

Type RM Length L Ch R = 1,14238,253,253,253
BEGIN DESCRIPTION:
Mapping XS 172daf84
END DESCRIPTION:
XS GIS Cut Line= 3
      1630462.24      6875801.51      1630405.81      6876541.38
      1630376.54      6877049.32
#Sta/Elev= 30
  4215.1 1784.12  4245.6 1783.16  4251.7 1782.38  4291.8 1780.67  4352.0 1779.16
  4582.7 1776.63  4602.7 1777.17  4612.7 1779.55  4622.8 1779.97  4632.8 1776.53
  4643.4 1775.91  4743.1 1774.88  4793.3 1773.82  4863.5 1773.55  4900.3 1772.52
  4905.3 1772.91  4963.8 1772.99  4981.1 1772.22  4981.5 1771.72  4986.0 1771.72
  4986.5 1772.22  5003.8 1772.76  5063.9 1772.45  5073.9 1772.88  5083.9 1774.35
  5104.0 1775.05  5230.6 1777.63  5244.2 1777.43  5334.4 1778.96  5465.9 1779.37
#Mann=3,-1,0
  4215.1    0.05       0  4981.1    0.03       0  4986.5    0.05       0
Bank Sta=4981.1,4986.5
Exp/Cntr=0.3,0.1

Type RM Length L Ch R = 1,13985,252,252,252
BEGIN DESCRIPTION:
Mapping XS dff64fa7
END DESCRIPTION:
XS GIS Cut Line= 2
      1629922.88      6876265.77      1630330.46      6876942.16
#Sta/Elev= 30
  4521.8 1778.89  4547.8 1778.45  4591.2 1776.70  4597.0 1776.86  4612.5 1776.41
  4618.4 1776.67  4649.4 1775.58  4722.9 1774.02  4839.6 1773.08  4888.3 1773.05
  4977.6 1770.81  4983.4 1771.05  4988.7 1770.66  4989.1 1770.16  4993.7 1770.16
  4994.1 1770.66  5014.5 1770.83  5049.8 1772.12  5099.9 1771.76  5131.0 1772.10
  5136.8 1772.54  5166.5 1773.27  5195.0 1774.71  5210.6 1775.03  5224.9 1776.05
  5231.9 1775.78  5247.5 1776.15  5259.9 1776.90  5290.2 1777.25  5311.5 1778.02
#Mann=3,-1,0
  4521.8    0.05       0  4988.7    0.05       0  4994.1    0.05       0
Bank Sta=4988.7,4994.1
Exp/Cntr=0.3,0.1

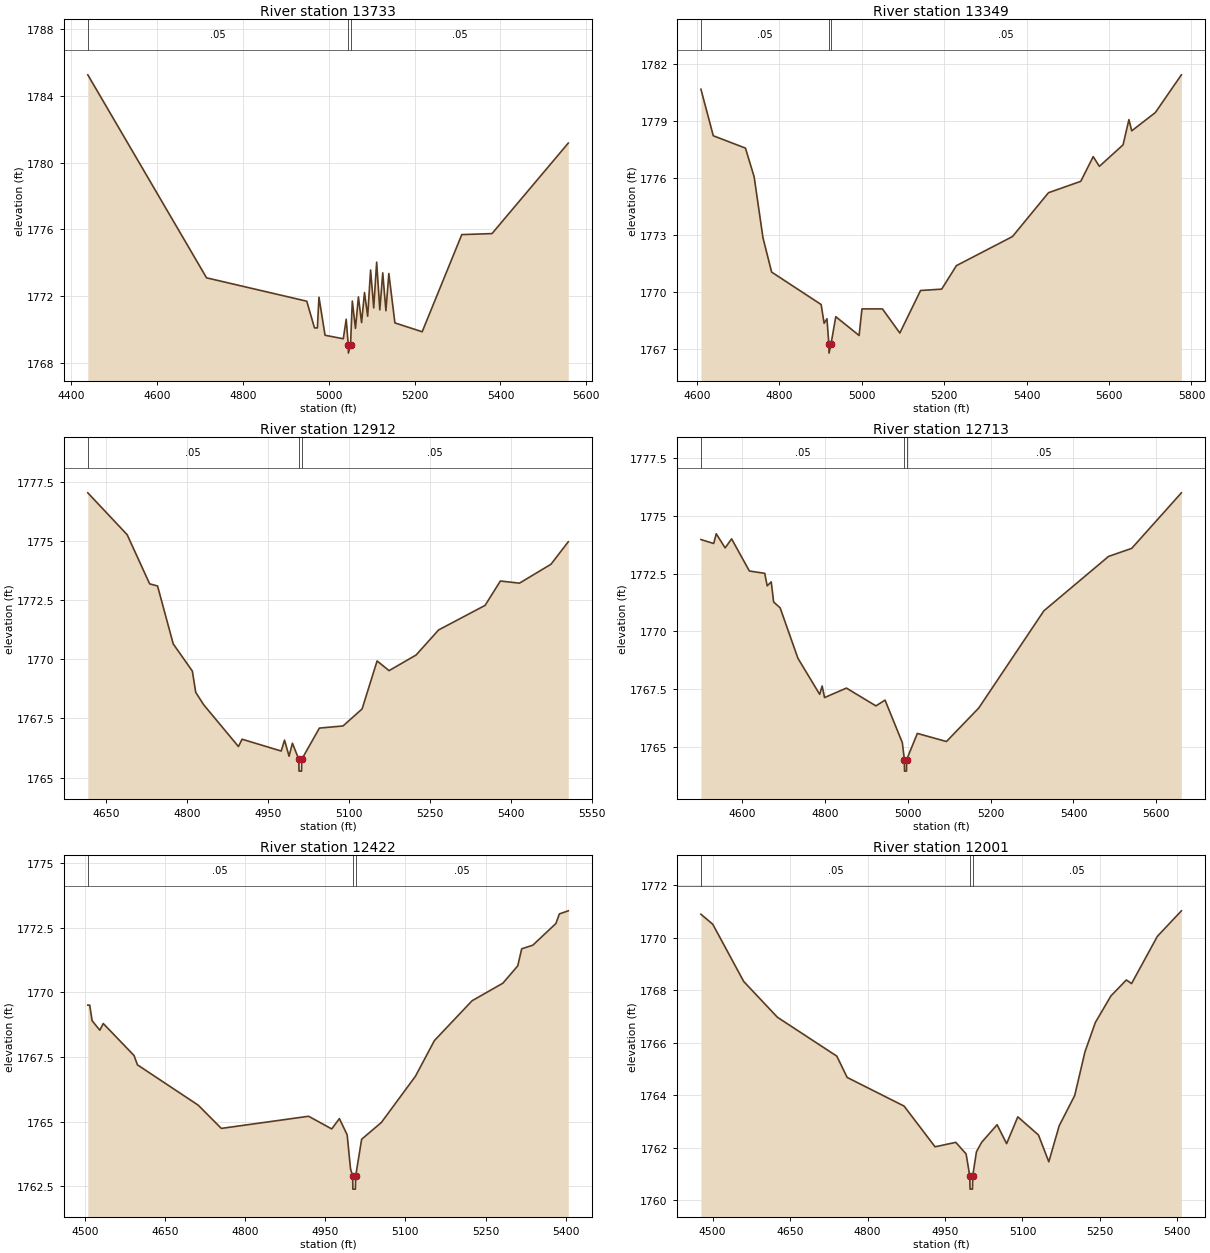
Type RM Length L Ch R = 1,13733,384,384,384
BEGIN DESCRIPTION:
Deadman 70 21.0
END DESCRIPTION:
XS GIS Cut Line= 3
      1629604.98      6876387.98      1629955.00      6876788.00
      1630387.52      6877186.27
#Sta/Elev= 30
  4438.5 1785.26  4715.2 1773.10  4948.7 1771.70  4966.7 1770.10  4973.4 1770.10
  4977.1 1771.94  4991.3 1769.66  5033.8 1769.45  5040.6 1770.62  5045.3 1769.09
  5045.7 1768.59  5050.7 1769.09  5054.8 1771.71  5062.2 1770.07  5069.0 1771.96
  5076.4 1770.42  5083.2 1772.22  5090.6 1770.80  5097.4 1773.57  5104.7 1771.30
  5111.5 1774.04  5118.9 1771.18  5125.7 1773.40  5133.1 1771.13  5139.9 1773.36
  5154.1 1770.40  5217.6 1769.87  5309.9 1775.69  5380.3 1775.75  5558.0 1781.17
#Mann=3,-1,0
  4438.5    0.05       0  5045.3    0.05       0  5050.7    0.05       0
Bank Sta=5045.3,5050.7
Exp/Cntr=0.3,0.1

Type RM Length L Ch R = 1,13349,437,437,437
BEGIN DESCRIPTION:
Mapping XS 2ecace08
END DESCRIPTION:
XS GIS Cut Line= 3
      1629436.16      6876804.35      1629818.10      6877168.93
      1630351.42      6877518.71
#Sta/Elev= 30
  4609.7 1780.67  4639.7 1778.22  4717.7 1777.57  4738.8 1776.06  4760.2 1772.85
  4781.2 1771.04  4901.4 1769.33  4908.6 1768.34  4915.5 1768.58  4920.0 1767.27
  4920.5 1766.77  4925.5 1767.27  4936.9 1768.69  4993.5 1767.70  5000.4 1769.10
  5050.1 1769.10  5092.3 1767.83  5142.6 1770.07  5193.8 1770.14  5229.7 1771.38
  5365.6 1772.91  5453.0 1775.22  5531.3 1775.82  5561.5 1777.12  5576.5 1776.61
  5633.9 1777.74  5648.2 1779.07  5655.0 1778.48  5712.2 1779.44  5775.5 1781.43
#Mann=3,-1,0
  4609.7    0.05       0  4920.0    0.03       0  4925.5    0.05       0
Bank Sta=4920,4925.5
Exp/Cntr=0.3,0.1

Type RM Length L Ch R = 1,12912,199,199,199
BEGIN DESCRIPTION:
Mapping XS 60d708ba
END DESCRIPTION:
XS GIS Cut Line= 2
      1629276.46      6877085.62      1629988.21      6877620.30
#Sta/Elev= 30
  4616.1 1777.04  4689.0 1775.27  4730.7 1773.19  4745.3 1773.10  4774.4 1770.65
  4809.8 1769.50  4816.1 1768.60  4830.7 1768.08  4895.2 1766.31  4901.9 1766.62
  4974.4 1766.12  4980.6 1766.58  4989.0 1765.90  4995.2 1766.45  5007.0 1765.77
  5007.5 1765.27  5012.1 1765.27  5012.5 1765.77  5045.2 1767.09  5088.9 1767.18
  5124.3 1767.90  5152.1 1769.93  5174.3 1769.52  5224.3 1770.18  5266.0 1771.24
  5352.2 1772.28  5380.5 1773.31  5415.9 1773.22  5474.3 1774.02  5506.3 1774.97
#Mann=3,-1,0
  4616.1    0.05       0  5007.0    0.03       0  5012.5    0.05       0
Bank Sta=5007,5012.5
Exp/Cntr=0.3,0.1

Type RM Length L Ch R = 1,12713,291,291,291
BEGIN DESCRIPTION:
Mapping XS 8c64dbe3
END DESCRIPTION:
XS GIS Cut Line= 3
      1629078.48      6877214.05      1629401.43      6877405.04
      1629997.19      6877914.21
#Sta/Elev= 30
  4501.4 1773.97  4532.2 1773.80  4538.3 1774.22  4559.8 1773.61  4575.4 1774.00
  4618.3 1772.61  4655.3 1772.51  4661.2 1771.97  4671.0 1772.14  4676.8 1771.27
  4692.4 1771.02  4735.3 1768.84  4787.8 1767.28  4793.8 1767.64  4799.6 1767.14
  4852.3 1767.55  4923.5 1766.78  4945.5 1767.03  4987.2 1765.19  4992.1 1764.46
  4992.5 1763.96  4997.2 1763.96  4997.7 1764.46  5023.4 1765.59  5093.6 1765.24
  5171.6 1766.69  5328.6 1770.89  5484.5 1773.24  5540.5 1773.59  5660.3 1775.99
#Mann=3,-1,0
  4501.4    0.05       0  4992.1    0.03       0  4997.7    0.05       0
Bank Sta=4992.1,4997.7
Exp/Cntr=0.3,0.1

Type RM Length L Ch R = 1,12422,421,421,421
BEGIN DESCRIPTION:
Mapping XS 76ed5eea
END DESCRIPTION:
XS GIS Cut Line= 2
      1629144.52      6877377.30      1629703.53      6878082.14
#Sta/Elev= 30
  4505.3 1769.51  4508.9 1769.51  4513.3 1768.91  4527.8 1768.54  4534.2 1768.80
  4591.9 1767.56  4598.2 1767.20  4712.0 1765.64  4755.3 1764.74  4918.7 1765.21
  4962.0 1764.72  4976.4 1765.12  4990.9 1764.49  4997.2 1763.18  5001.2 1762.89
  5001.6 1762.39  5006.3 1762.39  5006.8 1762.89  5018.0 1764.32  5055.0 1764.97
  5118.8 1766.76  5154.3 1768.14  5224.8 1769.68  5282.5 1770.36  5310.3 1771.03
  5317.7 1771.69  5338.5 1771.83  5381.8 1772.67  5388.2 1773.04  5404.9 1773.16
#Mann=3,-1,0
  4505.3    0.05       0  5001.2    0.05       0  5006.8    0.05       0
Bank Sta=5001.2,5006.8
Exp/Cntr=0.3,0.1

Type RM Length L Ch R = 1,12001,312,312,312
BEGIN DESCRIPTION:
Mapping XS fa2b35fd
END DESCRIPTION:
XS GIS Cut Line= 2
      1629033.37      6877325.14      1629074.98      6878254.41
#Sta/Elev= 30
  4477.5 1770.89  4500.4 1770.51  4560.4 1768.33  4625.6 1766.97  4740.6 1765.49
  4760.6 1764.68  4870.8 1763.59  4930.8 1762.04  4970.9 1762.21  4990.9 1761.77
  4998.0 1760.93  4998.5 1760.43  5003.2 1760.43  5003.7 1760.93  5010.9 1761.85
  5020.9 1762.21  5050.9 1762.88  5069.3 1762.16  5091.0 1763.18  5131.0 1762.49
  5151.0 1761.47  5171.1 1762.84  5201.1 1763.99  5221.1 1765.66  5241.1 1766.77
  5271.2 1767.78  5301.2 1768.39  5311.2 1768.25  5361.2 1770.05  5407.7 1771.02
#Mann=3,-1,0
  4477.5    0.05       0  4998.0    0.05       0  5003.7    0.05       0
Bank Sta=4998,5003.7
Exp/Cntr=0.3,0.1

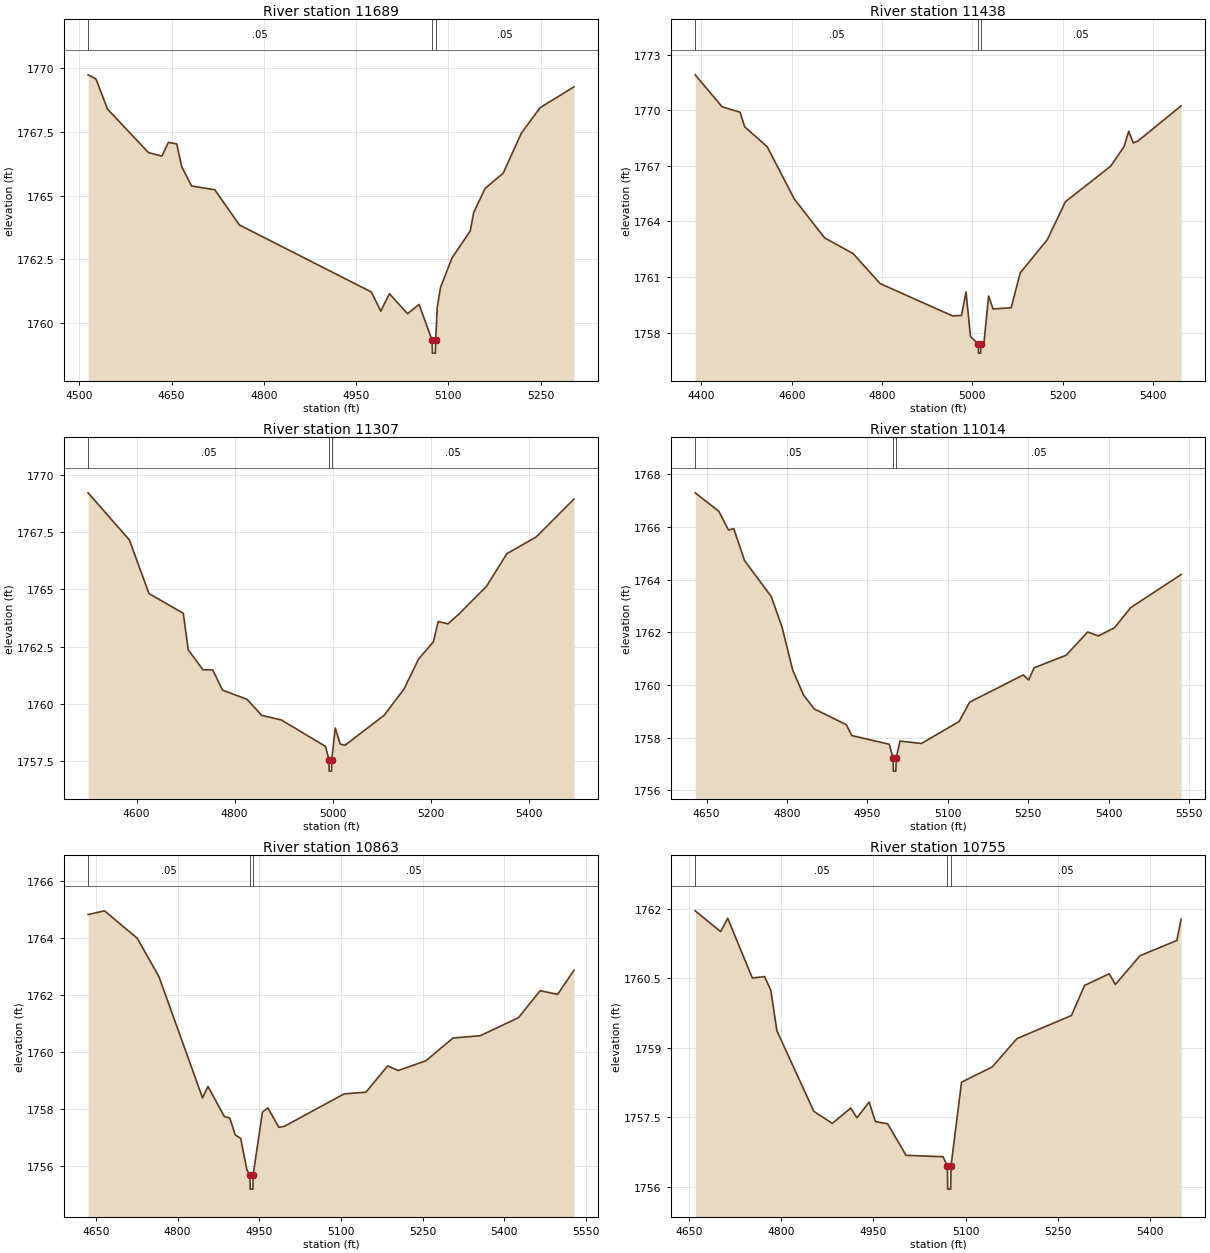
Type RM Length L Ch R = 1,11689,251,251,251
BEGIN DESCRIPTION:
Mapping XS 9a72a8e2
END DESCRIPTION:
XS GIS Cut Line= 2
      1628943.13      6877347.06      1628646.56      6878079.06
#Sta/Elev= 30
  4514.3 1769.74  4527.1 1769.58  4545.8 1768.40  4612.4 1766.69  4634.3 1766.55
  4644.8 1767.09  4658.4 1767.03  4666.4 1766.14  4682.5 1765.38  4720.3 1765.23
  4760.2 1763.85  4974.6 1761.22  4990.1 1760.47  5004.1 1761.15  5033.6 1760.37
  5052.3 1760.73  5073.5 1759.32  5074.0 1758.82  5078.8 1758.82  5079.2 1759.32
  5081.8 1760.62  5087.2 1761.40  5105.9 1762.56  5135.4 1763.61  5141.1 1764.34
  5159.5 1765.28  5189.0 1765.88  5218.5 1767.45  5249.0 1768.45  5304.1 1769.27
#Mann=3,-1,0
  4514.3    0.05       0  5073.5    0.05       0  5079.2    0.05       0
Bank Sta=5073.5,5079.2
Exp/Cntr=0.3,0.1

Type RM Length L Ch R = 1,11438,131,131,131
BEGIN DESCRIPTION:
Mapping XS 32c3baf0
END DESCRIPTION:
XS GIS Cut Line= 3
      1628536.85      6877078.63      1628536.85      6877366.85
      1628550.72      6878154.00
#Sta/Elev= 30
  4386.4 1771.91  4445.8 1770.19  4485.8 1769.89  4495.8 1769.11  4545.8 1768.03
  4605.8 1765.21  4672.7 1763.12  4735.8 1762.27  4795.8 1760.65  4955.8 1758.91
  4975.8 1758.93  4985.8 1760.20  4995.8 1757.79  5013.0 1757.40  5013.4 1756.90
  5018.2 1756.90  5018.7 1757.40  5025.8 1757.52  5035.8 1759.98  5045.8 1759.28
  5085.8 1759.35  5105.8 1761.23  5165.8 1763.02  5205.9 1765.07  5305.9 1766.98
  5335.9 1768.05  5345.9 1768.87  5355.9 1768.24  5365.9 1768.33  5461.9 1770.24
#Mann=3,-1,0
  4386.4    0.05       0  5013.0    0.03       0  5018.7    0.05       0
Bank Sta=5013,5018.7
Exp/Cntr=0.3,0.1

Type RM Length L Ch R = 1,11307,293,293,293
BEGIN DESCRIPTION:
Mapping XS 93e4f42f
END DESCRIPTION:
XS GIS Cut Line= 2
      1628425.74      6877123.78      1628443.07      6878114.93
#Sta/Elev= 30
  4501.1 1769.21  4585.3 1767.16  4625.3 1764.82  4695.3 1763.96  4705.4 1762.37
  4735.4 1761.50  4755.4 1761.49  4775.4 1760.61  4825.4 1760.21  4855.4 1759.51
  4895.4 1759.31  4985.4 1758.16  4992.5 1757.58  4993.0 1757.08  4997.8 1757.08
  4998.2 1757.58  5005.4 1758.96  5015.4 1758.26  5025.4 1758.21  5105.4 1759.52
  5145.4 1760.65  5175.4 1761.97  5205.4 1762.71  5215.4 1763.60  5235.4 1763.50
  5255.4 1763.88  5313.7 1765.13  5355.5 1766.56  5415.5 1767.29  5492.4 1768.94
#Mann=3,-1,0
  4501.1    0.05       0  4992.5    0.03       0  4998.2    0.05       0
Bank Sta=4992.5,4998.2
Exp/Cntr=0.3,0.1

Type RM Length L Ch R = 1,11014,151,151,151
BEGIN DESCRIPTION:
Mapping XS cd4028c3
END DESCRIPTION:
XS GIS Cut Line= 2
      1628179.21      6877096.04      1628196.57      6878002.27
#Sta/Elev= 30
  4628.7 1767.29  4672.8 1766.59  4690.7 1765.88  4700.7 1765.93  4720.7 1764.72
  4770.7 1763.35  4790.7 1762.19  4810.7 1760.56  4830.7 1759.62  4850.7 1759.09
  4910.7 1758.49  4920.7 1758.08  4990.7 1757.75  4997.8 1757.23  4998.3 1756.73
  5003.1 1756.73  5003.6 1757.23  5010.7 1757.87  5050.7 1757.78  5120.8 1758.61
  5140.8 1759.35  5240.8 1760.38  5250.8 1760.19  5260.8 1760.65  5320.8 1761.13
  5360.8 1762.01  5380.8 1761.86  5410.8 1762.17  5440.8 1762.93  5535.1 1764.19
#Mann=3,-1,0
  4628.7    0.05       0  4997.8    0.03       0  5003.6    0.05       0
Bank Sta=4997.8,5003.6
Exp/Cntr=0.3,0.1

Type RM Length L Ch R = 1,10863,108,108,108
BEGIN DESCRIPTION:
Mapping XS 2fa1e341
END DESCRIPTION:
XS GIS Cut Line= 2
      1628029.90      6877057.80      1628061.15      6877950.16
#Sta/Elev= 30
  4635.4 1764.82  4665.6 1764.95  4725.7 1763.99  4765.7 1762.64  4845.7 1758.39
  4855.7 1758.79  4885.7 1757.74  4895.8 1757.68  4905.8 1757.09  4915.8 1756.97
  4927.3 1755.86  4932.9 1755.69  4933.3 1755.19  4938.2 1755.19  4938.7 1755.69
  4955.8 1757.89  4965.8 1758.04  4985.8 1757.36  4995.8 1757.39  5105.9 1758.53
  5145.9 1758.59  5185.9 1759.51  5205.3 1759.35  5256.0 1759.69  5306.0 1760.49
  5356.0 1760.57  5426.1 1761.20  5466.1 1762.15  5498.2 1762.02  5528.3 1762.87
#Mann=3,-1,0
  4635.4    0.05       0  4932.9    0.03       0  4938.7    0.05       0
Bank Sta=4932.9,4938.7
Exp/Cntr=0.3,0.1

Type RM Length L Ch R = 1,10755,219,219,219
BEGIN DESCRIPTION:
Mapping XS d500a186
END DESCRIPTION:
XS GIS Cut Line= 2
      1627929.21      6877075.21      1627943.06      6877864.89
#Sta/Elev= 30
  4660.5 1761.96  4701.9 1761.51  4713.3 1761.80  4753.3 1760.51  4773.3 1760.54
  4783.3 1760.25  4793.3 1759.37  4853.3 1757.63  4883.3 1757.37  4913.3 1757.70
  4923.3 1757.49  4943.3 1757.83  4953.3 1757.41  4973.3 1757.36  5003.3 1756.68
  5063.3 1756.65  5070.5 1756.45  5070.9 1755.95  5075.8 1755.95  5076.3 1756.45
  5093.4 1758.26  5143.4 1758.59  5183.4 1759.20  5272.0 1759.70  5293.4 1760.35
  5333.4 1760.60  5343.4 1760.37  5383.4 1760.99  5443.4 1761.32  5450.3 1761.78
#Mann=3,-1,0
  4660.5    0.05       0  5070.5    0.03       0  5076.3    0.05       0
Bank Sta=5070.5,5076.3
Exp/Cntr=0.3,0.1