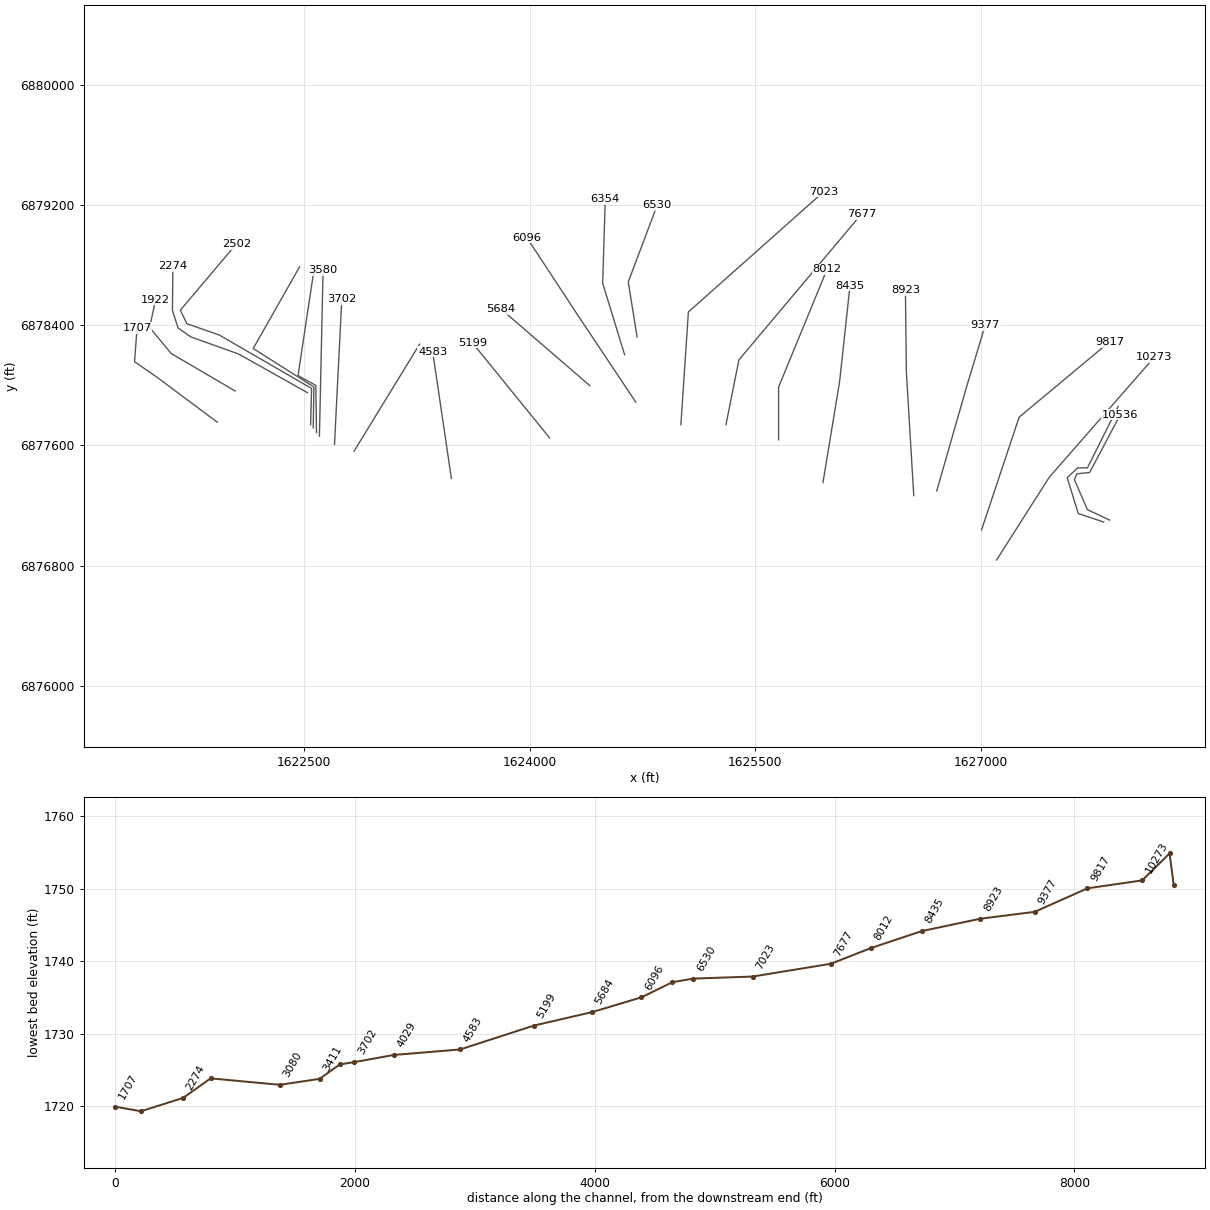
HEC-RAS study Deadman 70.prj: Deadman 70 Base Level Engineering

--- Deadman 70.g01 (geometry) --- (continued)

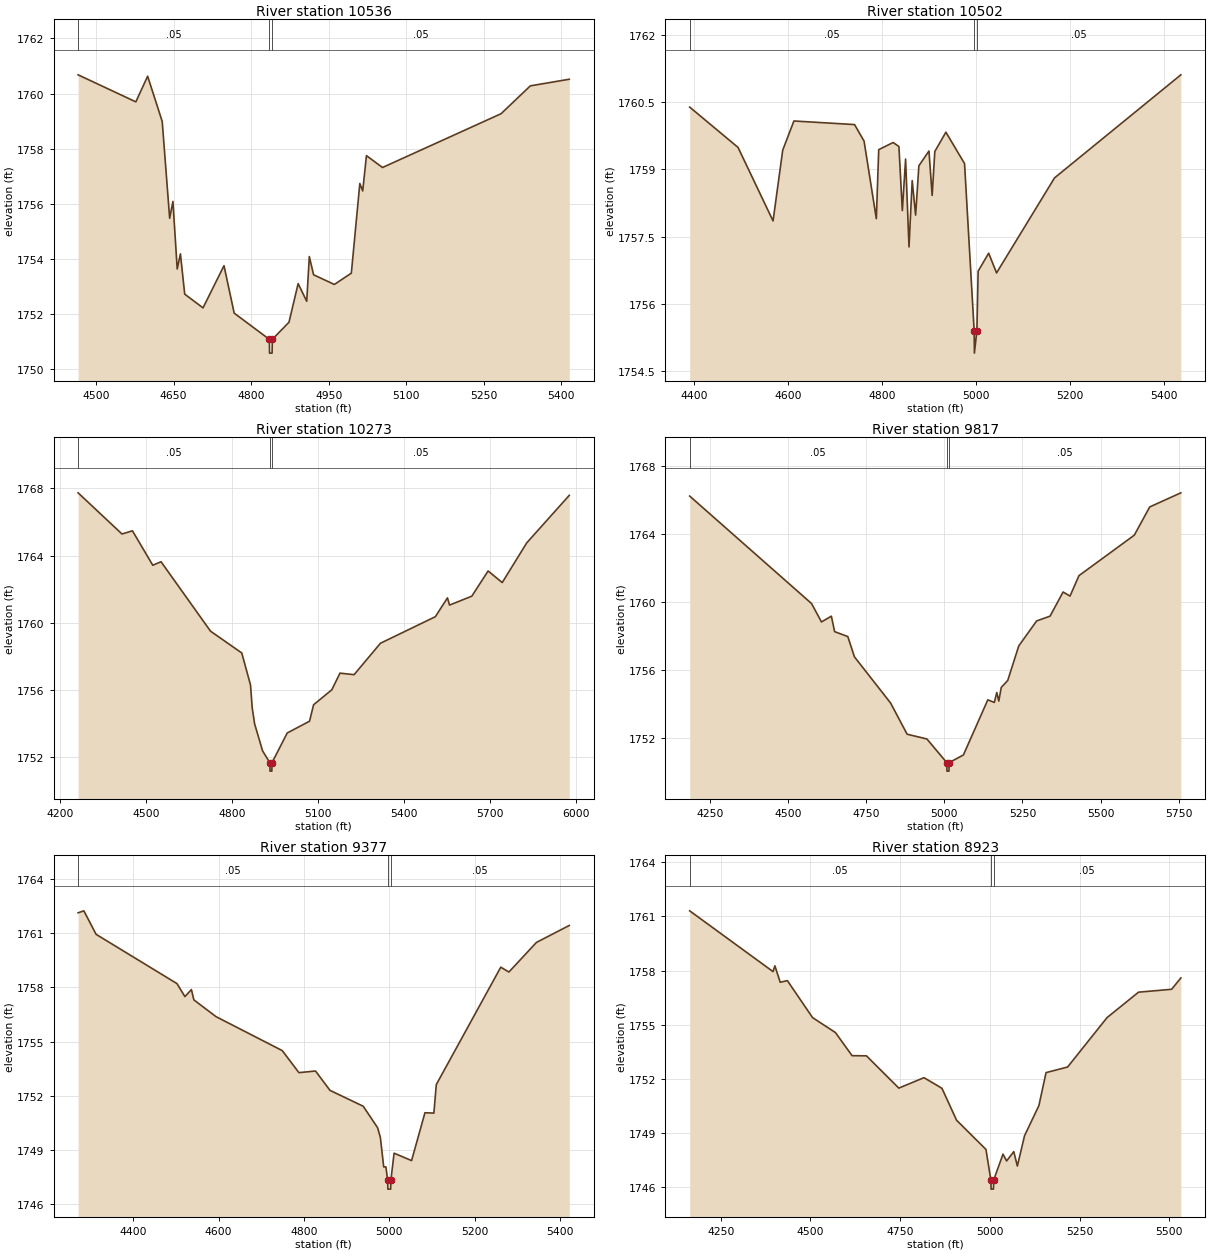
Type RM Length L Ch R = 1,10536,34,34,34
BEGIN DESCRIPTION:
Mapping XS c4753ba4
END DESCRIPTION:
XS GIS Cut Line= 6
      1627856.91      6877103.49      1627709.37      6877172.92
      1627622.56      6877372.58      1627639.92      6877411.64
      1627723.96      6877420.04      1627927.93      6877804.54
#Sta/Elev= 30
  4465.2 1760.68  4576.9 1759.70  4599.7 1760.63  4627.9 1758.99  4642.3 1755.48
  4648.6 1756.09  4656.9 1753.64  4663.1 1754.19  4671.4 1752.73  4706.8 1752.23
  4747.4 1753.76  4767.1 1752.04  4835.1 1751.09  4835.5 1750.59  4840.4 1750.59
  4840.9 1751.09  4873.1 1751.71  4890.8 1753.11  4907.4 1752.47  4912.4 1754.09
  4920.7 1753.43  4960.9 1753.08  4993.7 1753.49  5010.1 1756.74  5015.7 1756.47
  5022.9 1757.75  5054.0 1757.32  5283.3 1759.27  5339.9 1760.28  5415.2 1760.52
#Mann=3,-1,0
  4465.2    0.05       0  4835.1    0.05       0  4840.9    0.05       0
Bank Sta=4835.1,4840.9
Exp/Cntr=0.3,0.1

Type RM Length L Ch R = 1,10502,229,229,229
BEGIN DESCRIPTION:
Mapping XS 6f701eb3
END DESCRIPTION:
XS GIS Cut Line= 6
      1627817.83      6877090.47      1627648.60      6877146.88
      1627574.82      6877385.60      1627644.26      6877450.70
      1627709.37      6877450.70      1627913.35      6877858.67
#Sta/Elev= 30
  4389.8 1760.39  4492.8 1759.49  4567.4 1757.85  4588.0 1759.43  4611.8 1760.08
  4741.0 1760.00  4761.3 1759.63  4787.4 1757.90  4792.5 1759.44  4823.2 1759.60
  4835.5 1759.51  4842.8 1758.08  4849.7 1759.23  4857.0 1757.27  4863.8 1758.75
  4871.1 1757.98  4878.0 1759.08  4899.5 1759.41  4906.3 1758.42  4912.0 1759.40
  4935.6 1759.83  4975.3 1759.13  4995.8 1755.40  4996.3 1754.90  5001.6 1755.40
  5004.3 1756.73  5026.7 1757.13  5043.5 1756.69  5167.0 1758.81  5436.1 1761.11
#Mann=3,-1,0
  4389.8    0.05       0  4995.8    0.05       0  5001.6    0.05       0
Bank Sta=4995.8,5001.6
Exp/Cntr=0.3,0.1

Type RM Length L Ch R = 1,10273,456,456,456
BEGIN DESCRIPTION:
Deadman 70 15.0
END DESCRIPTION:
XS GIS Cut Line= 3
      1627104.99      6876837.98      1627455.00      6877388.00
      1628155.03      6878188.03
#Sta/Elev= 30
  4261.8 1767.73  4415.1 1765.28  4451.5 1765.47  4522.6 1763.42  4551.4 1763.63
  4724.1 1759.50  4833.3 1758.20  4863.8 1756.30  4869.7 1754.94  4878.2 1753.98
  4906.1 1752.37  4931.4 1751.67  4931.9 1751.17  4938.3 1751.17  4938.8 1751.67
  4992.0 1753.44  5069.9 1754.14  5084.1 1755.12  5147.7 1756.01  5176.2 1757.00
  5225.5 1756.91  5317.6 1758.78  5509.3 1760.36  5551.6 1761.48  5558.7 1761.05
  5636.5 1761.58  5693.4 1763.08  5742.8 1762.39  5828.2 1764.75  5976.8 1767.58
#Mann=3,-1,0
  4261.8    0.05       0  4931.4    0.05       0  4938.8    0.05       0
Bank Sta=4931.4,4938.8
Exp/Cntr=0.3,0.1

Type RM Length L Ch R = 1,9817,440,440,440
BEGIN DESCRIPTION:
Deadman 70 14.0
END DESCRIPTION:
XS GIS Cut Line= 3
      1627005.00      6877037.99      1627255.00      6877788.00
      1627854.99      6878288.00
#Sta/Elev= 30
  4185.4 1766.25  4575.4 1759.93  4607.1 1758.85  4638.7 1759.19  4649.2 1758.28
  4691.4 1757.99  4712.5 1756.80  4828.4 1754.08  4881.1 1752.25  4944.4 1751.97
  5008.1 1750.58  5008.6 1750.08  5015.0 1750.08  5015.5 1750.58  5061.2 1751.03
  5139.3 1754.27  5160.2 1754.12  5168.0 1754.70  5174.5 1754.20  5182.3 1755.00
  5203.1 1755.41  5238.3 1757.44  5295.6 1758.91  5338.5 1759.19  5380.2 1760.61
  5402.3 1760.37  5430.9 1761.57  5608.0 1763.95  5657.4 1765.61  5757.0 1766.44
#Mann=3,-1,0
  4185.4    0.05       0  5008.1    0.05       0  5015.5    0.05       0
Bank Sta=5008.1,5015.5
Exp/Cntr=0.3,0.1

Type RM Length L Ch R = 1,9377,454,454,454
BEGIN DESCRIPTION:
Deadman 70 13.0
END DESCRIPTION:
XS GIS Cut Line= 3
      1626707.00      6877297.44      1626905.00      6877988.00
      1627029.90      6878401.57
#Sta/Elev= 30
  4270.9 1762.13  4284.4 1762.24  4313.0 1760.94  4502.5 1758.21  4521.1 1757.49
  4536.3 1757.88  4542.0 1757.31  4594.0 1756.38  4749.1 1754.50  4788.1 1753.28
  4827.0 1753.37  4860.8 1752.30  4938.7 1751.42  4972.4 1750.23  4978.9 1749.69
  4986.7 1748.06  4991.9 1748.06  4995.9 1747.33  4996.4 1746.83  5003.0 1746.83
  5003.5 1747.33  5011.0 1748.82  5052.0 1748.41  5083.3 1751.06  5104.2 1751.04
  5109.9 1752.62  5260.9 1759.12  5279.9 1758.85  5344.4 1760.49  5421.3 1761.43
#Mann=3,-1,0
  4270.9    0.05       0  4995.9    0.03       0  5003.5    0.05       0
Bank Sta=4995.9,5003.5
Exp/Cntr=0.3,0.1

Type RM Length L Ch R = 1,8923,488,488,488
BEGIN DESCRIPTION:
Deadman 70 12.0
END DESCRIPTION:
XS GIS Cut Line= 3
      1626554.21      6877266.16      1626505.00      6878088.00
      1626498.66      6878633.65
#Sta/Elev= 30
  4163.4 1761.31  4395.7 1757.94  4400.9 1758.26  4415.7 1757.35  4435.7 1757.44
  4505.9 1755.39  4569.7 1754.56  4616.0 1753.28  4656.1 1753.27  4746.3 1751.48
  4816.4 1752.06  4866.5 1751.47  4907.3 1749.70  4989.2 1748.08  5002.9 1746.38
  5003.4 1745.88  5010.1 1745.88  5010.6 1746.38  5036.7 1747.82  5046.7 1747.44
  5066.7 1747.96  5076.7 1747.16  5096.7 1748.84  5136.7 1750.51  5156.7 1752.34
  5216.7 1752.65  5326.7 1755.39  5414.4 1756.80  5506.7 1756.96  5532.4 1757.59
#Mann=3,-1,0
  4163.4    0.05       0  5002.9    0.05       0  5010.6    0.05       0
Bank Sta=5002.9,5010.6
Exp/Cntr=0.3,0.1

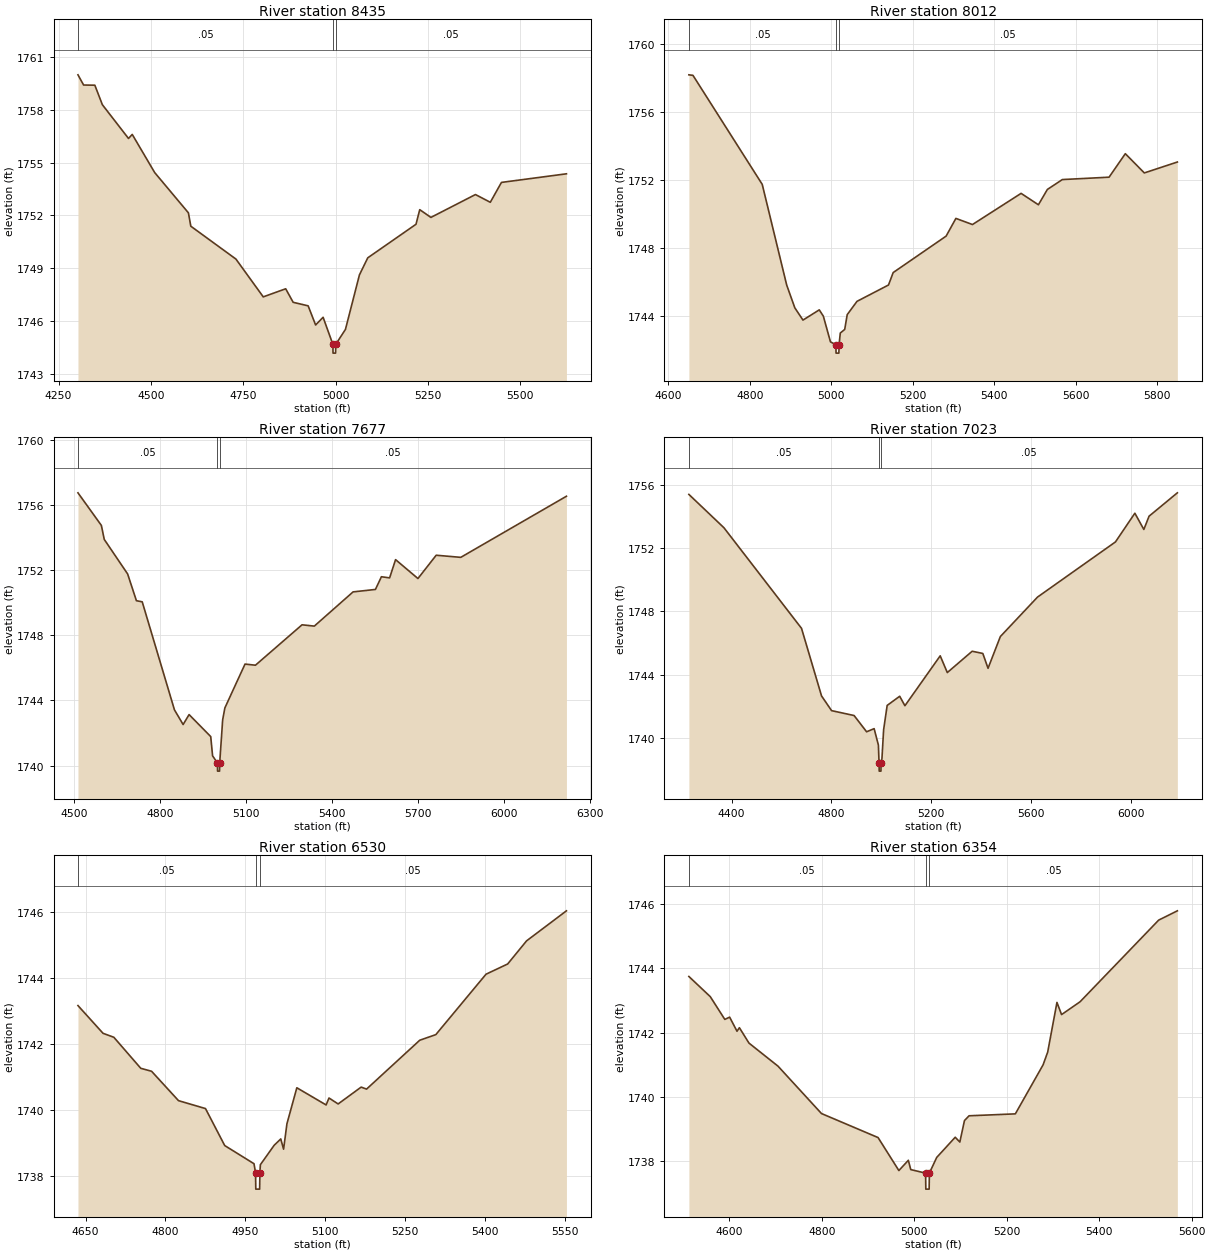
Type RM Length L Ch R = 1,8435,423,423,423
BEGIN DESCRIPTION:
Deadman 70 11.0
END DESCRIPTION:
XS GIS Cut Line= 3
      1625950.04      6877352.93      1626061.15      6878026.57
      1626130.00      6878663.02
#Sta/Elev= 30
  4302.5 1760.00  4317.8 1759.42  4348.2 1759.41  4368.6 1758.30  4439.4 1756.38
  4449.5 1756.61  4510.3 1754.44  4601.6 1752.15  4608.1 1751.39  4730.3 1749.52
  4804.3 1747.37  4865.1 1747.83  4885.3 1747.06  4925.9 1746.86  4946.1 1745.77
  4966.4 1746.21  4992.8 1744.67  4993.3 1744.17  5000.2 1744.17  5000.7 1744.67
  5026.9 1745.52  5064.8 1748.62  5087.3 1749.59  5218.0 1751.50  5228.1 1752.33
  5258.4 1751.89  5379.0 1753.19  5419.2 1752.75  5449.4 1753.88  5625.4 1754.37
#Mann=3,-1,0
  4302.5    0.05       0  4992.8    0.03       0  5000.7    0.05       0
Bank Sta=4992.8,5000.7
Exp/Cntr=0.3,0.1

Type RM Length L Ch R = 1,8012,335,335,335
BEGIN DESCRIPTION:
Deadman 70 10.0
END DESCRIPTION:
XS GIS Cut Line= 3
      1625655.00      6877637.99      1625655.00      6877988.00
      1625977.79      6878773.02
#Sta/Elev= 30
  4650.4 1758.18  4660.4 1758.15  4830.4 1751.75  4890.4 1745.84  4910.4 1744.50
  4930.4 1743.78  4970.4 1744.38  4980.4 1744.01  4997.9 1742.50  5011.1 1742.34
  5011.6 1741.84  5018.5 1741.84  5019.0 1742.34  5022.0 1743.02  5032.8 1743.23
  5039.0 1744.10  5063.0 1744.88  5140.3 1745.84  5151.8 1746.57  5281.7 1748.71
  5305.7 1749.75  5346.4 1749.39  5465.7 1751.22  5508.2 1750.55  5530.2 1751.45
  5566.9 1752.03  5681.6 1752.17  5721.5 1753.55  5768.1 1752.42  5849.2 1753.06
#Mann=3,-1,0
  4650.4    0.05       0  5011.1    0.05       0  5019.0    0.05       0
Bank Sta=5011.1,5019
Exp/Cntr=0.3,0.1

Type RM Length L Ch R = 1,7677,654,654,654
BEGIN DESCRIPTION:
Deadman 70 9.0
END DESCRIPTION:
XS GIS Cut Line= 3
      1625305.00      6877737.99      1625391.02      6878168.93
      1626205.00      6879137.99
#Sta/Elev= 30
  4514.0 1756.74  4595.7 1754.74  4605.8 1753.88  4687.4 1751.76  4718.0 1750.12
  4738.3 1750.05  4850.8 1743.42  4881.1 1742.52  4901.9 1743.13  4977.4 1741.78
  4983.9 1740.60  5000.8 1740.16  5001.3 1739.66  5008.2 1739.66  5008.7 1740.16
  5019.1 1742.81  5026.8 1743.54  5097.1 1746.23  5133.5 1746.16  5296.1 1748.64
  5339.0 1748.56  5474.3 1750.66  5552.3 1750.81  5573.2 1751.59  5601.8 1751.52
  5622.6 1752.64  5700.7 1751.48  5764.4 1752.91  5850.2 1752.78  6219.0 1756.53
#Mann=3,-1,0
  4514.0    0.05       0  5000.8    0.05       0  5008.7    0.05       0
Bank Sta=5000.8,5008.7
Exp/Cntr=0.3,0.1

Type RM Length L Ch R = 1,7023,493,493,493
BEGIN DESCRIPTION:
Deadman 70 8.0
END DESCRIPTION:
XS GIS Cut Line= 3
      1625005.00      6877737.99      1625055.00      6878488.00
      1625954.97      6879287.97
#Sta/Elev= 30
  4229.3 1755.41  4369.6 1753.30  4680.3 1746.93  4760.5 1742.65  4800.6 1741.72
  4890.8 1741.41  4940.9 1740.38  4971.0 1740.58  4988.1 1739.54  4990.8 1738.39
  4991.3 1737.89  4998.3 1737.89  4998.8 1738.39  5002.3 1738.68  5009.0 1740.51
  5023.2 1742.05  5073.4 1742.63  5094.3 1742.03  5235.6 1745.19  5264.0 1744.13
  5363.6 1745.48  5406.2 1745.34  5427.1 1744.40  5476.4 1746.41  5625.3 1748.91
  5937.2 1752.40  6015.0 1754.22  6050.9 1753.19  6071.8 1754.03  6185.1 1755.51
#Mann=3,-1,0
  4229.3    0.05       0  4990.8    0.05       0  4998.8    0.05       0
Bank Sta=4990.8,4998.8
Exp/Cntr=0.3,0.1

Type RM Length L Ch R = 1,6530,176,176,176
BEGIN DESCRIPTION:
Deadman 70 7.0
END DESCRIPTION:
XS GIS Cut Line= 3
      1624713.70      6878321.46      1624655.00      6878688.00
      1624847.84      6879199.33
#Sta/Elev= 30
  4635.6 1743.17  4682.7 1742.33  4703.0 1742.21  4753.6 1741.27  4773.9 1741.18
  4824.5 1740.29  4875.2 1740.05  4911.3 1738.93  4966.3 1738.38  4969.2 1738.11
  4969.7 1737.61  4976.9 1737.61  4977.4 1738.11  4978.3 1738.35  5004.3 1738.94
  5016.6 1739.13  5021.9 1738.82  5028.2 1739.59  5046.8 1740.68  5101.8 1740.16
  5107.2 1740.37  5124.4 1740.19  5167.6 1740.70  5177.8 1740.64  5277.7 1742.12
  5307.9 1742.29  5402.2 1744.12  5442.9 1744.43  5478.4 1745.13  5553.3 1746.04
#Mann=3,-1,0
  4635.6    0.05       0  4969.2    0.05       0  4977.4    0.05       0
Bank Sta=4969.2,4977.4
Exp/Cntr=0.3,0.1

Type RM Length L Ch R = 1,6354,258,258,258
BEGIN DESCRIPTION:
Mapping XS 29ed7f13
END DESCRIPTION:
XS GIS Cut Line= 3
      1624630.59      6878203.70      1624484.77      6878679.35
      1624502.13      6879238.38
#Sta/Elev= 30
  4512.3 1743.75  4558.6 1743.12  4590.0 1742.41  4600.5 1742.48  4616.4 1742.04
  4621.6 1742.15  4642.3 1741.67  4705.1 1740.95  4799.2 1739.47  4921.6 1738.72
  4966.6 1737.69  4987.1 1738.01  4992.3 1737.72  5024.4 1737.61  5024.9 1737.11
  5032.1 1737.11  5032.6 1737.61  5048.5 1738.10  5088.5 1738.73  5098.5 1738.58
  5108.5 1739.25  5118.5 1739.40  5218.6 1739.46  5278.6 1740.99  5288.6 1741.39
  5308.6 1742.94  5318.6 1742.56  5358.6 1742.96  5528.7 1745.51  5569.1 1745.80
#Mann=3,-1,0
  4512.3    0.05       0  5024.4    0.05       0  5032.6    0.05       0
Bank Sta=5024.4,5032.6
Exp/Cntr=0.3,0.1

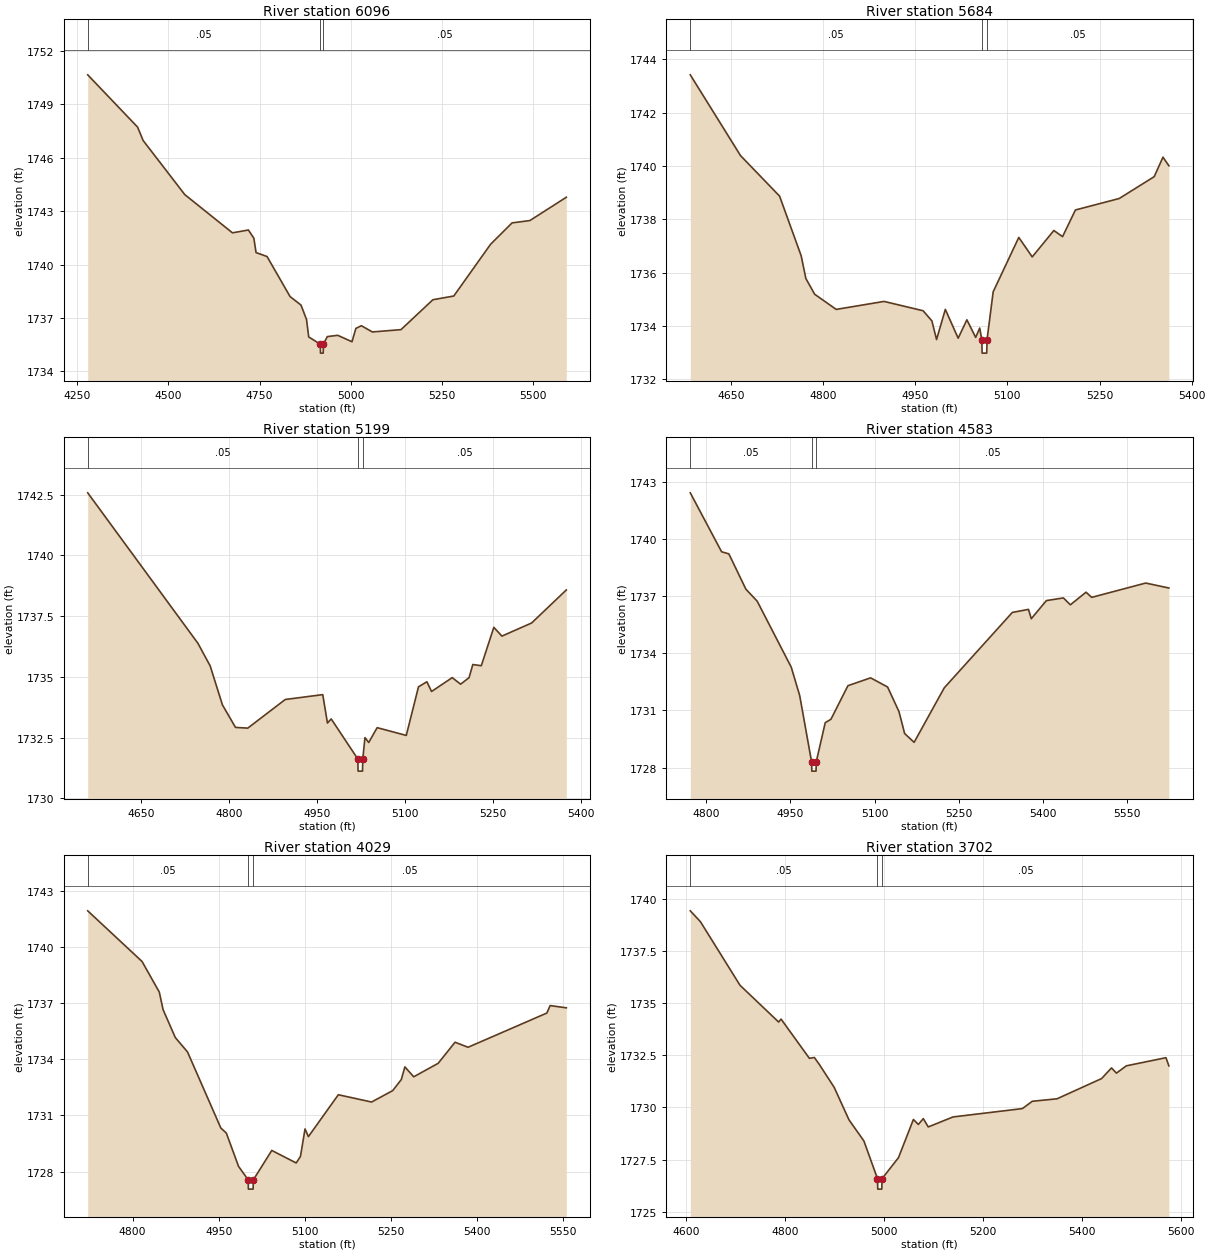
Type RM Length L Ch R = 1,6096,412,412,412
BEGIN DESCRIPTION:
Deadman 70 6.0
END DESCRIPTION:
XS GIS Cut Line= 3
      1624705.02      6877887.97      1624305.00      6878488.00
      1623981.29      6878981.44
#Sta/Elev= 30
  4279.2 1750.66  4415.9 1747.72  4431.0 1746.97  4545.1 1743.93  4675.8 1741.78
  4719.4 1741.94  4734.4 1741.48  4740.4 1740.67  4770.5 1740.45  4833.6 1738.20
  4863.6 1737.72  4878.7 1736.91  4884.7 1735.93  4916.5 1735.52  4917.0 1735.02
  4924.4 1735.02  4924.9 1735.52  4935.7 1735.95  4964.3 1736.02  5003.3 1735.66
  5013.9 1736.41  5029.0 1736.56  5059.2 1736.21  5137.5 1736.34  5224.9 1738.02
  5282.2 1738.23  5383.1 1741.14  5441.9 1742.34  5490.7 1742.47  5590.5 1743.78
#Mann=3,-1,0
  4279.2    0.05       0  4916.5    0.05       0  4924.9    0.05       0
Bank Sta=4916.5,4924.9
Exp/Cntr=0.3,0.1

Type RM Length L Ch R = 1,5684,485,485,485
BEGIN DESCRIPTION:
Mapping XS 277ae180
END DESCRIPTION:
XS GIS Cut Line= 2
      1624399.70      6877997.62      1623809.54      6878506.57
#Sta/Elev= 30
  4583.6 1743.42  4665.4 1740.39  4729.0 1738.87  4764.2 1736.63  4771.8 1735.78
  4786.1 1735.19  4821.2 1734.62  4899.1 1734.92  4962.7 1734.57  4977.0 1734.19
  4984.6 1733.49  4998.9 1734.62  5019.8 1733.54  5034.0 1734.23  5048.3 1733.57
  5054.9 1733.92  5058.3 1733.48  5058.8 1732.98  5066.3 1732.98  5066.8 1733.48
  5076.8 1735.28  5118.5 1737.32  5140.4 1736.59  5175.6 1737.58  5189.8 1737.35
  5210.7 1738.35  5282.0 1738.78  5339.0 1739.60  5353.3 1740.33  5362.9 1740.01
#Mann=3,-1,0
  4583.6    0.05       0  5058.3    0.05       0  5066.8    0.05       0
Bank Sta=5058.3,5066.8
Exp/Cntr=0.3,0.1

Type RM Length L Ch R = 1,5199,616,616,616
BEGIN DESCRIPTION:
Mapping XS a5b2822b
END DESCRIPTION:
XS GIS Cut Line= 2
      1624131.45      6877650.83      1623617.41      6878283.91
#Sta/Elev= 30
  4559.0 1742.58  4746.9 1736.38  4767.7 1735.45  4788.5 1733.85  4810.8 1732.92
  4831.7 1732.89  4895.6 1734.07  4959.5 1734.27  4967.5 1733.10  4973.9 1733.27
  5019.2 1731.62  5019.7 1731.12  5027.2 1731.12  5027.7 1731.62  5031.4 1732.50
  5037.8 1732.30  5052.2 1732.91  5101.8 1732.59  5122.6 1734.59  5136.9 1734.80
  5144.9 1734.40  5180.1 1734.97  5194.4 1734.70  5208.8 1734.97  5215.2 1735.51
  5229.6 1735.46  5251.0 1737.04  5264.8 1736.68  5315.4 1737.22  5374.5 1738.58
#Mann=3,-1,0
  4559.0    0.05       0  5019.2    0.05       0  5027.7    0.05       0
Bank Sta=5019.2,5027.7
Exp/Cntr=0.3,0.1

Type RM Length L Ch R = 1,4583,554,554,554
BEGIN DESCRIPTION:
Mapping XS 6f5abeca
END DESCRIPTION:
XS GIS Cut Line= 2
      1623478.46      6877379.93      1623354.00      6878224.10
#Sta/Elev= 30
  4771.5 1742.41  4827.3 1739.32  4840.3 1739.21  4870.6 1737.36  4890.8 1736.73
  4951.5 1733.27  4966.6 1731.78  4987.7 1728.32  4988.2 1727.82  4995.7 1727.82
  4996.2 1728.32  5012.1 1730.36  5022.3 1730.54  5052.6 1732.30  5093.0 1732.71
  5123.3 1732.23  5143.6 1730.94  5153.7 1729.79  5170.6 1729.33  5224.4 1732.19
  5345.7 1736.14  5374.5 1736.30  5379.5 1735.81  5406.4 1736.76  5436.7 1736.90
  5449.2 1736.54  5477.1 1737.20  5487.2 1736.93  5583.5 1737.68  5624.8 1737.42
#Mann=3,-1,0
  4771.5    0.05       0  4987.7    0.05       0  4996.2    0.05       0
Bank Sta=4987.7,4996.2
Exp/Cntr=0.3,0.1

Type RM Length L Ch R = 1,4029,327,327,327
BEGIN DESCRIPTION:
Mapping XS 8685d128
END DESCRIPTION:
XS GIS Cut Line= 2
      1622830.93      6877561.47      1623266.83      6878273.54
#Sta/Elev= 30
  4721.6 1741.95  4816.4 1739.24  4846.5 1737.60  4853.1 1736.66  4874.4 1735.17
  4895.7 1734.40  4953.8 1730.33  4963.4 1730.06  4984.7 1728.28  5001.4 1727.56
  5001.9 1727.06  5010.1 1727.06  5010.6 1727.56  5042.7 1729.13  5085.3 1728.46
  5092.7 1728.81  5100.7 1730.28  5106.6 1729.87  5158.8 1732.11  5216.8 1731.72
  5253.6 1732.33  5268.6 1732.92  5274.9 1733.60  5290.3 1733.07  5332.9 1733.79
  5362.4 1734.92  5385.1 1734.65  5522.5 1736.48  5528.3 1736.88  5556.5 1736.76
#Mann=3,-1,0
  4721.6    0.05       0  5001.4    0.05       0  5010.6    0.05       0
Bank Sta=5001.4,5010.6
Exp/Cntr=0.3,0.1

Type RM Length L Ch R = 1,3702,122,122,122
BEGIN DESCRIPTION:
Mapping XS 07569c2c
END DESCRIPTION:
XS GIS Cut Line= 2
      1622700.86      6877607.49      1622749.58      6878573.86
#Sta/Elev= 30
  4608.3 1739.42  4628.8 1738.90  4708.9 1735.85  4786.9 1734.09  4791.9 1734.23
  4849.1 1732.35  4859.1 1732.39  4869.1 1732.06  4899.2 1730.96  4929.2 1729.40
  4959.3 1728.39  4986.8 1726.58  4987.3 1726.08  4995.5 1726.08  4996.0 1726.58
  5029.3 1727.59  5059.4 1729.42  5069.4 1729.18  5079.4 1729.46  5089.4 1729.06
  5139.5 1729.54  5279.7 1729.94  5299.7 1730.29  5349.8 1730.41  5439.9 1731.38
  5459.9 1731.89  5469.9 1731.64  5489.9 1731.99  5570.0 1732.38  5575.9 1731.99
#Mann=3,-1,0
  4608.3    0.05       0  4986.8    0.05       0  4996.0    0.05       0
Bank Sta=4986.8,4996
Exp/Cntr=0.3,0.1

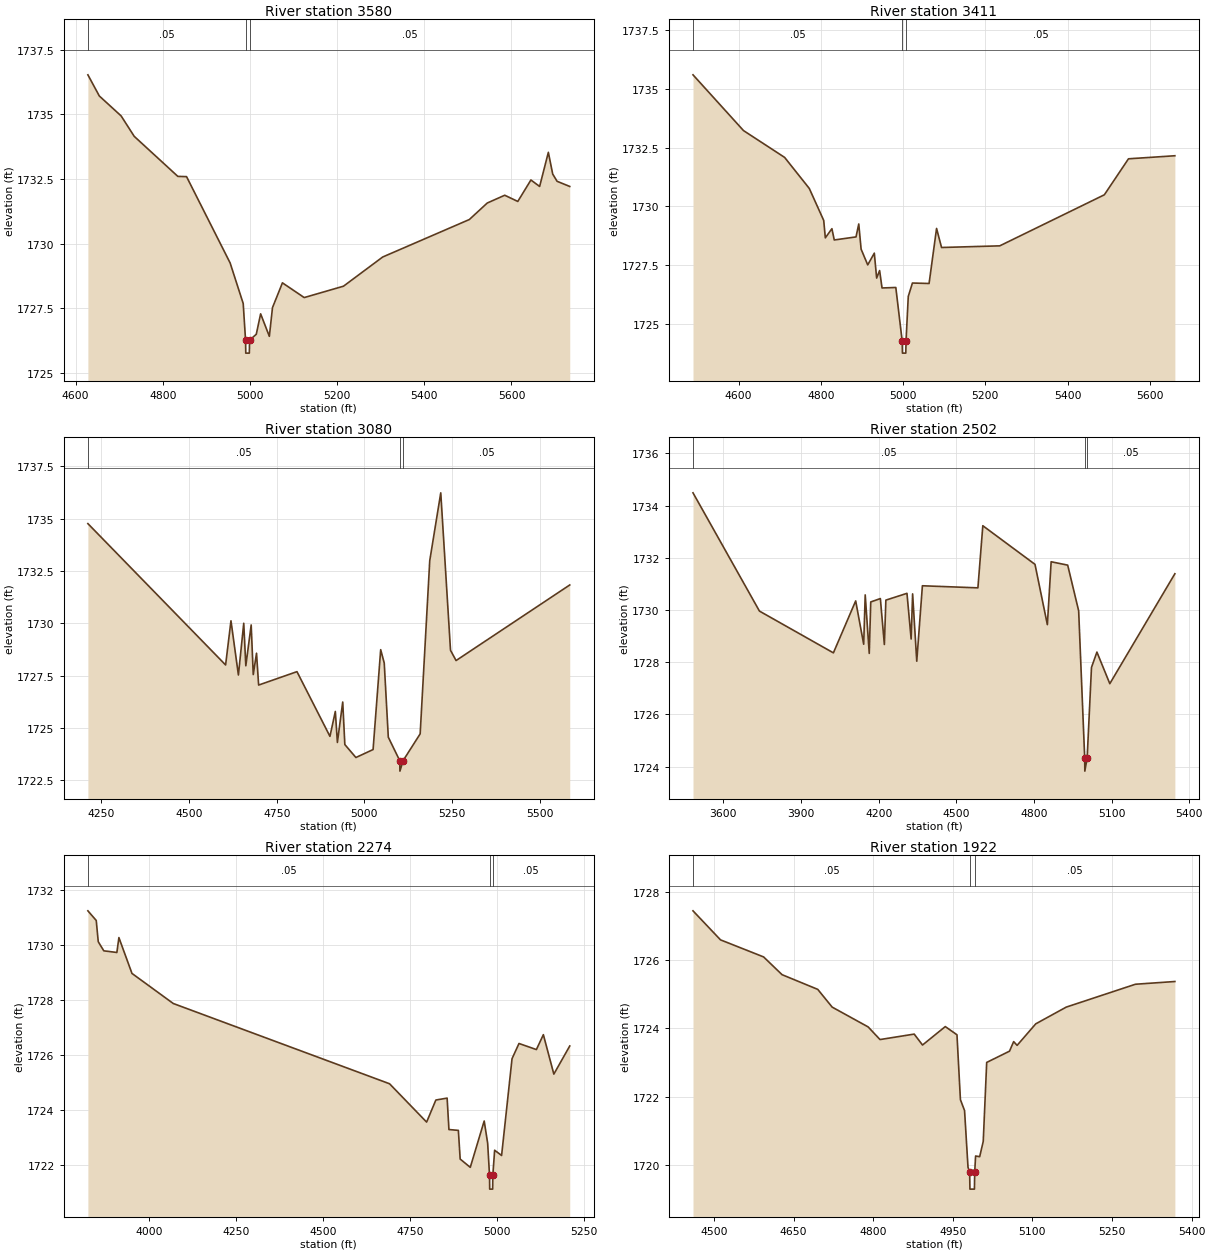
Type RM Length L Ch R = 1,3580,169,169,169
BEGIN DESCRIPTION:
Mapping XS 8b88fefd
END DESCRIPTION:
XS GIS Cut Line= 2
      1622600.61      6877661.69      1622625.00      6878767.12
#Sta/Elev= 30
  4628.0 1736.53  4654.3 1735.71  4704.3 1734.94  4734.3 1734.15  4834.4 1732.60
  4854.4 1732.59  4954.4 1729.25  4984.4 1727.68  4989.8 1726.26  4990.3 1725.76
  4998.5 1725.76  4999.0 1726.26  5014.4 1726.49  5024.4 1727.28  5044.4 1726.41
  5051.6 1727.52  5074.4 1728.48  5124.4 1727.91  5214.5 1728.35  5304.5 1729.48
  5503.3 1730.93  5544.5 1731.57  5584.5 1731.87  5614.5 1731.63  5644.6 1732.46
  5664.6 1732.21  5684.6 1733.53  5694.6 1732.69  5704.6 1732.41  5733.7 1732.21
#Mann=3,-1,0
  4628.0    0.05       0  4989.8    0.05       0  4999.0    0.05       0
Bank Sta=4989.8,4999
Exp/Cntr=0.3,0.1

Type RM Length L Ch R = 1,3411,331,331,331
BEGIN DESCRIPTION:
Mapping XS 31d3bd3a
END DESCRIPTION:
XS GIS Cut Line= 4
      1622581.18      6877685.20      1622576.72      6877999.63
      1622458.25      6878065.16      1622566.18      6878778.99
#Sta/Elev= 30
  4489.2 1735.59  4612.0 1733.22  4712.0 1732.08  4772.0 1730.76  4807.1 1729.40
  4811.0 1728.66  4827.0 1729.05  4832.7 1728.57  4885.6 1728.70  4892.3 1729.25
  4898.0 1728.18  4914.1 1727.51  4930.1 1728.01  4935.8 1726.95  4943.0 1727.27
  4948.9 1726.53  4982.4 1726.55  4998.0 1724.26  4998.5 1723.76  5006.7 1723.76
  5007.2 1724.26  5012.7 1726.17  5022.8 1726.74  5063.3 1726.72  5081.5 1729.06
  5093.6 1728.25  5235.2 1728.32  5489.5 1730.49  5548.2 1732.02  5661.0 1732.15
#Mann=3,-1,0
  4489.2    0.05       0  4998.0    0.05       0  5007.2    0.05       0
Bank Sta=4998,5007.2
Exp/Cntr=0.3,0.1

Type RM Length L Ch R = 1,3080,578,578,578
BEGIN DESCRIPTION:
Mapping XS 539c6ddd
END DESCRIPTION:
XS GIS Cut Line= 4
      1622559.48      6877717.72      1622563.82      6877988.99
      1622160.18      6878245.07      1622468.35      6878787.62
#Sta/Elev= 30
  4211.9 1734.76  4604.4 1728.01  4619.7 1730.12  4640.9 1727.53  4656.1 1730.00
  4662.0 1727.97  4677.3 1729.92  4683.2 1727.55  4692.5 1728.57  4698.5 1727.05
  4807.8 1727.69  4901.8 1724.60  4917.1 1725.79  4923.0 1724.31  4938.2 1726.24
  4944.2 1724.21  4975.7 1723.59  5024.7 1723.97  5046.4 1728.74  5056.5 1728.10
  5068.1 1724.56  5100.7 1723.44  5101.2 1722.94  5110.2 1723.44  5158.9 1724.72
  5186.2 1732.99  5217.6 1736.23  5245.4 1728.71  5261.2 1728.22  5585.2 1731.83
#Mann=3,-1,0
  4211.9    0.05       0  5100.7    0.05       0  5110.2    0.05       0
Bank Sta=5100.7,5110.2
Exp/Cntr=0.3,0.1

Type RM Length L Ch R = 1,2502,228,228,228
BEGIN DESCRIPTION:
Mapping XS 9511adcf
END DESCRIPTION:
XS GIS Cut Line= 6
      1622542.06      6877738.20      1622548.44      6877979.20
      1621933.13      6878335.26      1621719.00      6878409.74
      1621675.56      6878499.73      1622047.95      6878940.40
#Sta/Elev= 30
  3482.8 1734.49  3739.5 1729.96  4025.1 1728.36  4111.2 1730.35  4142.1 1728.69
  4148.0 1730.58  4163.6 1728.34  4169.4 1730.31  4206.5 1730.44  4222.0 1728.68
  4227.8 1730.38  4309.3 1730.64  4325.4 1728.89  4331.1 1730.62  4347.1 1728.04
  4368.9 1730.93  4583.3 1730.85  4602.3 1733.23  4803.8 1731.75  4851.6 1729.44
  4866.2 1731.85  4930.1 1731.72  4972.5 1729.97  4995.8 1724.33  4996.3 1723.83
  5005.3 1724.33  5022.0 1727.80  5043.0 1728.39  5092.8 1727.18  5344.1 1731.39
#Mann=3,-1,0
  3482.8    0.05       0  4995.8    0.05       0  5005.3    0.05       0
Bank Sta=4995.8,5005.3
Exp/Cntr=0.3,0.1

Type RM Length L Ch R = 1,2274,352,352,352
BEGIN DESCRIPTION:
Mapping XS e32a95c3
END DESCRIPTION:
XS GIS Cut Line= 6
      1622520.96      6877951.27      1622063.46      6878208.03
      1621743.83      6878322.85      1621660.04      6878381.81
      1621622.80      6878499.73      1621625.90      6878793.75
#Sta/Elev= 30
  3825.0 1731.23  3849.0 1730.88  3854.8 1730.11  3870.7 1729.78  3908.3 1729.72
  3914.1 1730.26  3951.7 1728.96  4070.3 1727.87  4691.7 1724.96  4798.2 1723.57
  4824.7 1724.37  4857.1 1724.44  4862.3 1723.30  4889.4 1723.27  4894.6 1722.23
  4923.6 1721.93  4963.6 1723.61  4973.6 1722.80  4978.9 1721.64  4979.4 1721.14
  4987.9 1721.14  4988.4 1721.64  4993.6 1722.55  5013.6 1722.36  5043.6 1725.87
  5063.6 1726.42  5113.6 1726.20  5133.6 1726.74  5163.7 1725.31  5209.4 1726.33
#Mann=3,-1,0
  3825.0    0.05       0  4978.9    0.05       0  4988.4    0.05       0
Bank Sta=4978.9,4988.4
Exp/Cntr=0.3,0.1

Type RM Length L Ch R = 1,1922,215,215,215
BEGIN DESCRIPTION:
Mapping XS 3c10a8de
END DESCRIPTION:
XS GIS Cut Line= 4
      1622039.73      6877962.45      1621614.38      6878211.70
      1621471.11      6878384.82      1621511.31      6878570.61
#Sta/Elev= 30
  4460.6 1727.44  4512.4 1726.59  4593.6 1726.09  4628.4 1725.57  4695.6 1725.14
  4722.8 1724.62  4790.6 1724.04  4812.9 1723.67  4877.3 1723.83  4893.0 1723.51
  4935.9 1724.05  4957.9 1723.81  4964.4 1721.91  4972.2 1721.59  4978.7 1719.93
  4981.8 1719.79  4982.3 1719.29  4990.8 1719.29  4991.3 1719.79  4993.0 1720.26
  5000.7 1720.24  5007.4 1720.69  5013.9 1723.00  5056.9 1723.33  5064.7 1723.61
  5071.2 1723.50  5106.3 1724.13  5163.7 1724.62  5294.1 1725.29  5368.4 1725.37
#Mann=3,-1,0
  4460.6    0.05       0  4981.8    0.05       0  4991.3    0.05       0
Bank Sta=4981.8,4991.3
Exp/Cntr=0.3,0.1

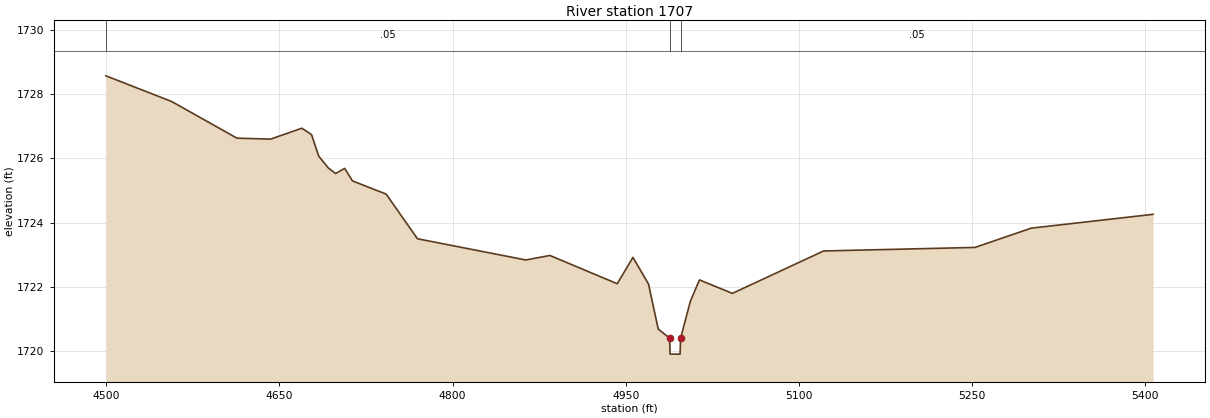
Type RM Length L Ch R = 1,1707,300,300,300
BEGIN DESCRIPTION:
Mapping XS c22be045
END DESCRIPTION:
XS GIS Cut Line= 4
      1621920.69      6877754.97      1621520.13      6878054.00
      1621370.76      6878156.83      1621387.61      6878381.78
#Sta/Elev= 30
  4499.8 1728.57  4556.8 1727.77  4613.3 1726.63  4642.4 1726.60  4669.5 1726.94
  4677.9 1726.74  4684.1 1726.07  4692.5 1725.70  4698.7 1725.53  4706.6 1725.69
  4713.3 1725.30  4742.5 1724.89  4769.6 1723.50  4863.4 1722.84  4884.3 1722.98
  4942.6 1722.10  4956.2 1722.92  4969.7 1722.09  4978.1 1720.69  4987.9 1720.41
  4988.4 1719.91  4997.0 1719.91  4997.5 1720.41  5005.9 1721.55  5013.8 1722.22
  5042.3 1721.80  5121.3 1723.12  5252.4 1723.23  5301.1 1723.83  5406.6 1724.26
#Mann=3,-1,0
  4499.8    0.05       0  4987.9    0.05       0  4997.5    0.05       0
Bank Sta=4987.9,4997.5
Exp/Cntr=0.3,0.1