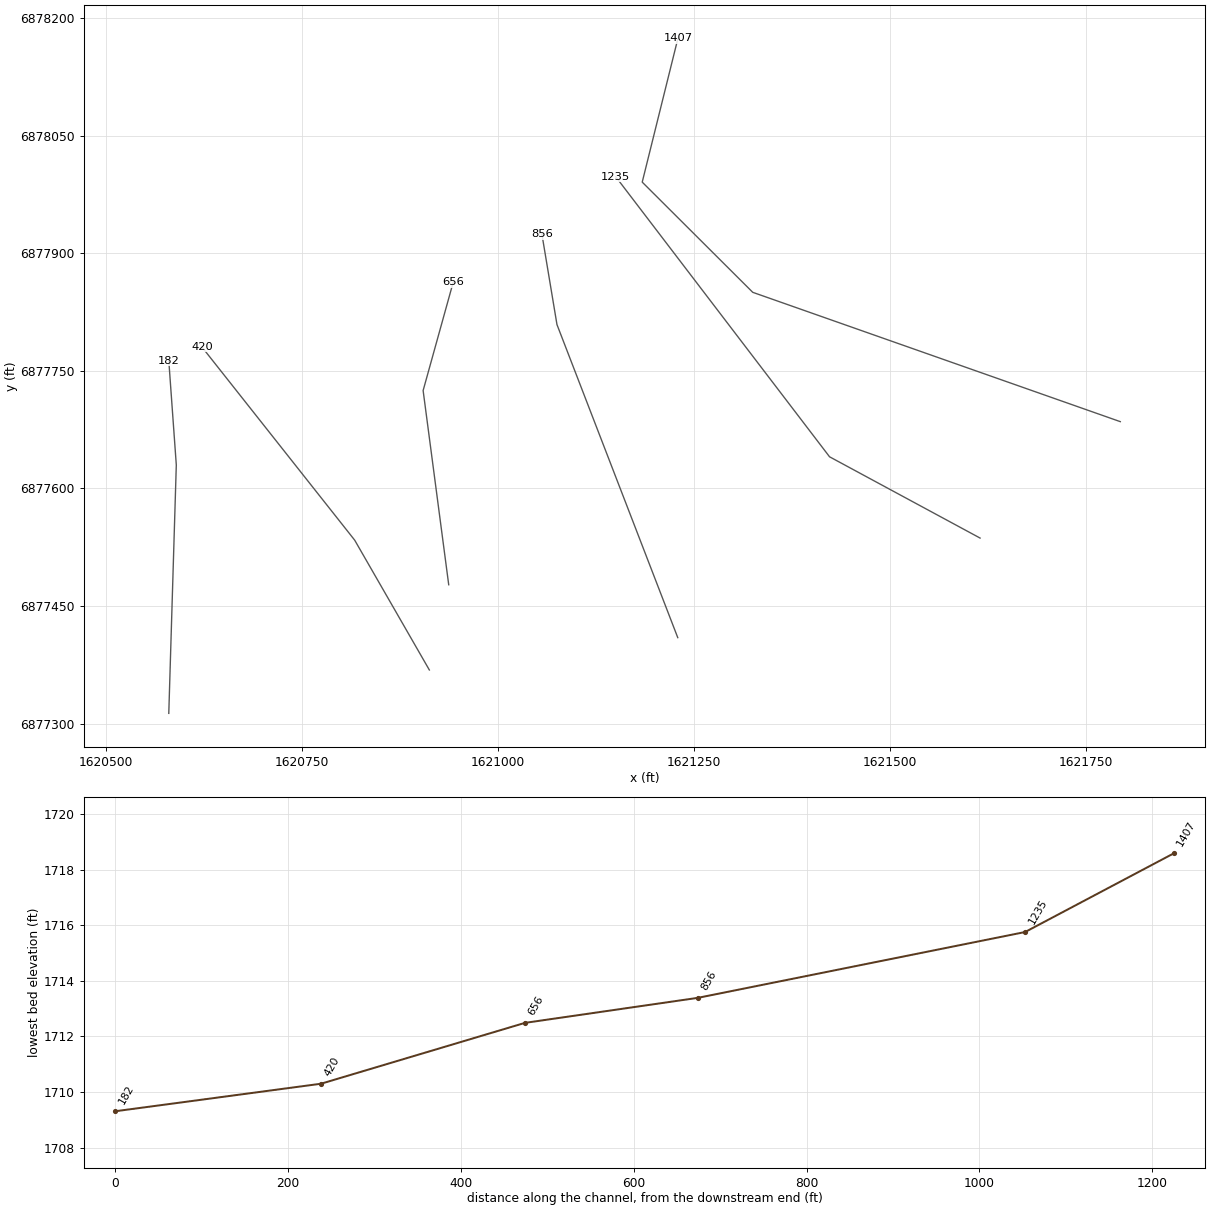
HEC-RAS study Deadman 70.prj: Deadman 70 Base Level Engineering

--- Deadman 70.g01 (geometry) --- (continued)

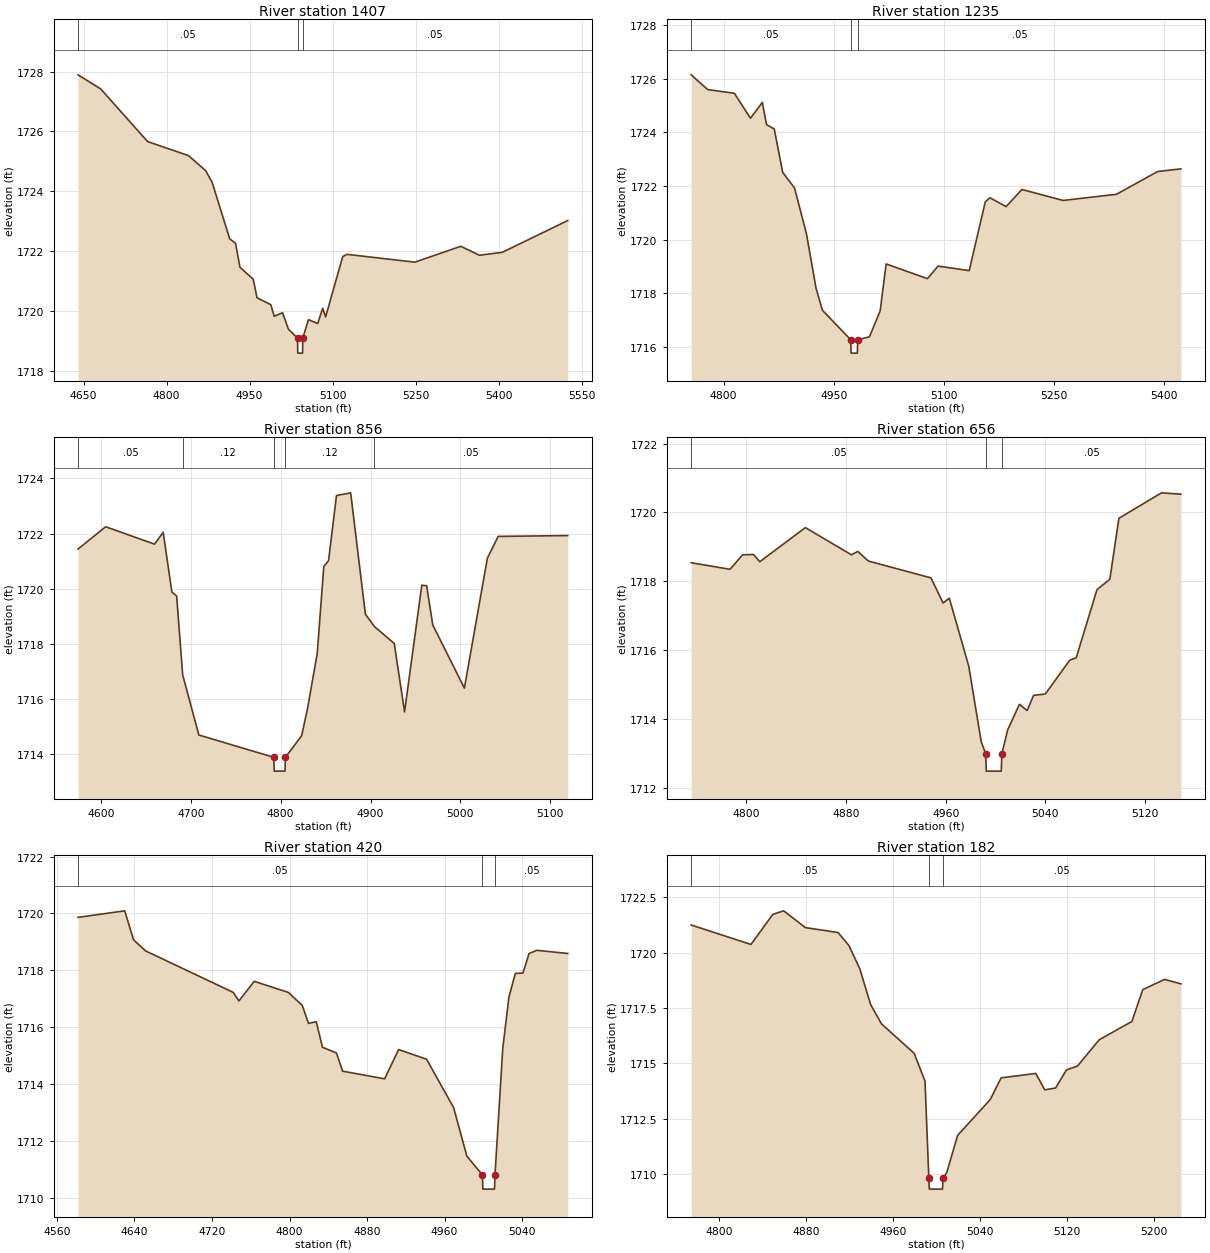
Type RM Length L Ch R = 1,1407,172,172,172
BEGIN DESCRIPTION:
Mapping XS bd43da8b
END DESCRIPTION:
XS GIS Cut Line= 4
      1621793.61      6877685.06      1621324.82      6877850.01
      1621183.85      6877990.56      1621229.39      6878173.96
#Sta/Elev= 30
  4640.0 1727.89  4680.9 1727.42  4765.7 1725.66  4839.7 1725.19  4870.6 1724.69
  4882.3 1724.30  4914.1 1722.41  4924.7 1722.26  4932.6 1721.46  4956.6 1721.06
  4963.5 1720.44  4988.4 1720.21  4994.5 1719.82  5009.6 1719.94  5020.2 1719.39
  5036.6 1719.09  5037.1 1718.59  5045.7 1718.59  5046.2 1719.09  5056.4 1719.71
  5073.2 1719.58  5082.1 1720.09  5087.4 1719.80  5118.4 1721.82  5126.2 1721.89
  5248.6 1721.63  5331.7 1722.16  5365.5 1721.86  5406.9 1721.96  5525.0 1723.02
#Mann=3,-1,0
  4640.0    0.05       0  5036.6    0.03       0  5046.2    0.05       0
Bank Sta=5036.6,5046.2
Exp/Cntr=0.3,0.1

Type RM Length L Ch R = 1,1235,379,379,379
BEGIN DESCRIPTION:
Deadman 70 2.0
END DESCRIPTION:
XS GIS Cut Line= 3
      1621614.76      6877536.58      1621422.77      6877640.25
      1621150.12      6877997.38
#Sta/Elev= 30
  4755.8 1726.15  4778.3 1725.60  4814.7 1725.46  4836.6 1724.53  4852.8 1725.12
  4858.5 1724.29  4869.0 1724.13  4880.5 1722.51  4896.6 1721.93  4912.8 1720.23
  4926.0 1718.18  4934.7 1717.36  4973.2 1716.26  4973.7 1715.76  4982.3 1715.76
  4982.8 1716.26  4998.8 1716.37  5013.4 1717.34  5021.5 1719.09  5077.8 1718.54
  5092.3 1719.01  5134.7 1718.84  5156.7 1721.41  5163.0 1721.56  5185.0 1721.23
  5206.6 1721.87  5262.8 1721.46  5335.4 1721.69  5391.6 1722.54  5423.3 1722.64
#Mann=3,-1,0
  4755.8    0.05       0  4973.2    0.05       0  4982.8    0.05       0
Bank Sta=4973.2,4982.8
Exp/Cntr=0.3,0.1

Type RM Length L Ch R = 1,856,200,200,200
BEGIN DESCRIPTION:
Mapping XS 857dd75b
END DESCRIPTION:
XS GIS Cut Line= 3
      1621229.18      6877409.58      1621075.11      6877808.87
      1621055.84      6877924.49
#Sta/Elev= 30
  4574.4 1721.44  4605.1 1722.25  4659.6 1721.62  4669.2 1722.05  4678.9 1719.88
  4684.2 1719.74  4690.9 1716.88  4708.9 1714.70  4792.3 1713.89  4792.8 1713.39
  4804.8 1713.39  4805.3 1713.89  4823.4 1714.68  4830.0 1715.68  4840.7 1717.66
  4848.0 1720.81  4853.3 1721.02  4862.1 1723.38  4877.9 1723.48  4894.3 1719.08
  4904.4 1718.63  4926.4 1718.02  4937.9 1715.54  4957.1 1720.13  4962.5 1720.11
  4969.3 1718.69  5004.5 1716.40  5030.1 1721.11  5042.1 1721.90  5119.6 1721.93
#Mann=5,-1,0
  4574.4    0.05       0  4690.9    0.12       0  4792.3    0.05       0
  4805.3    0.12       0  4904.4    0.05       0
Bank Sta=4792.3,4805.3
Exp/Cntr=0.3,0.1

Type RM Length L Ch R = 1,656,236,236,236
BEGIN DESCRIPTION:
Mapping XS a6b10bc8
END DESCRIPTION:
XS GIS Cut Line= 3
      1620937.04      6877477.05      1620904.40      6877724.73
      1620942.80      6877862.97
#Sta/Elev= 30
  4755.6 1718.54  4786.8 1718.35  4796.9 1718.77  4805.7 1718.78  4810.7 1718.57
  4847.3 1719.56  4884.3 1718.77  4889.4 1718.87  4897.8 1718.59  4948.2 1718.10
  4957.9 1717.37  4962.9 1717.51  4978.5 1715.54  4988.5 1713.35  4992.1 1712.99
  4992.6 1712.49  5004.6 1712.49  5005.1 1712.99  5009.7 1713.68  5019.2 1714.43
  5025.4 1714.25  5030.6 1714.69  5040.0 1714.73  5059.6 1715.71  5064.8 1715.78
  5081.5 1717.76  5091.8 1718.06  5099.1 1719.83  5133.3 1720.57  5148.9 1720.53
#Mann=3,-1,0
  4755.6    0.05       0  4992.1    0.05       0  5005.1    0.05       0
Bank Sta=4992.1,5005.1
Exp/Cntr=0.3,0.1

Type RM Length L Ch R = 1,420,238,238,238
BEGIN DESCRIPTION:
Mapping XS cb20b4f8
END DESCRIPTION:
XS GIS Cut Line= 3
      1620912.34      6877368.34      1620817.11      6877533.91
      1620622.15      6877780.43
#Sta/Elev= 30
  4581.8 1719.86  4630.0 1720.09  4639.1 1719.07  4651.5 1718.68  4742.0 1717.22
  4747.8 1716.92  4763.6 1717.61  4798.8 1717.22  4813.2 1716.76  4819.6 1716.13
  4827.6 1716.19  4834.0 1715.29  4848.4 1715.09  4854.8 1714.45  4898.1 1714.18
  4912.6 1715.21  4941.4 1714.87  4969.3 1713.17  4983.0 1711.46  4999.0 1710.80
  4999.5 1710.30  5011.5 1710.30  5012.0 1710.80  5020.0 1715.24  5026.4 1717.06
  5033.0 1717.89  5040.8 1717.90  5047.2 1718.59  5055.2 1718.70  5087.1 1718.59
#Mann=3,-1,0
  4581.8    0.05       0  4999.0    0.05       0  5012.0    0.05       0
Bank Sta=4999,5012
Exp/Cntr=0.3,0.1

Type RM Length L Ch R = 1,182,0,0,0
BEGIN DESCRIPTION:
Deadman 70 1.0
END DESCRIPTION:
XS GIS Cut Line= 3
      1620580.00      6877312.98      1620589.59      6877629.83
      1620580.00      6877762.99
#Sta/Elev= 30
  4774.1 1721.25  4829.1 1720.37  4849.2 1721.73  4859.2 1721.89  4879.2 1721.13
  4909.2 1720.91  4919.2 1720.32  4929.2 1719.27  4939.2 1717.65  4949.2 1716.78
  4979.2 1715.45  4989.2 1714.19  4992.7 1709.81  4993.2 1709.31  5005.3 1709.31
  5005.8 1709.81  5009.2 1710.06  5019.2 1711.74  5049.2 1713.36  5059.2 1714.34
  5091.1 1714.54  5099.3 1713.80  5109.3 1713.88  5119.3 1714.70  5129.4 1714.87
  5149.4 1716.06  5179.5 1716.89  5189.5 1718.33  5209.6 1718.79  5224.6 1718.59
#Mann=3,-1,0
  4774.1    0.05       0  4992.7    0.05       0  5005.8    0.05       0
Bank Sta=4992.7,5005.8
Exp/Cntr=0.3,0.1

Chan Stop Cuts=-1