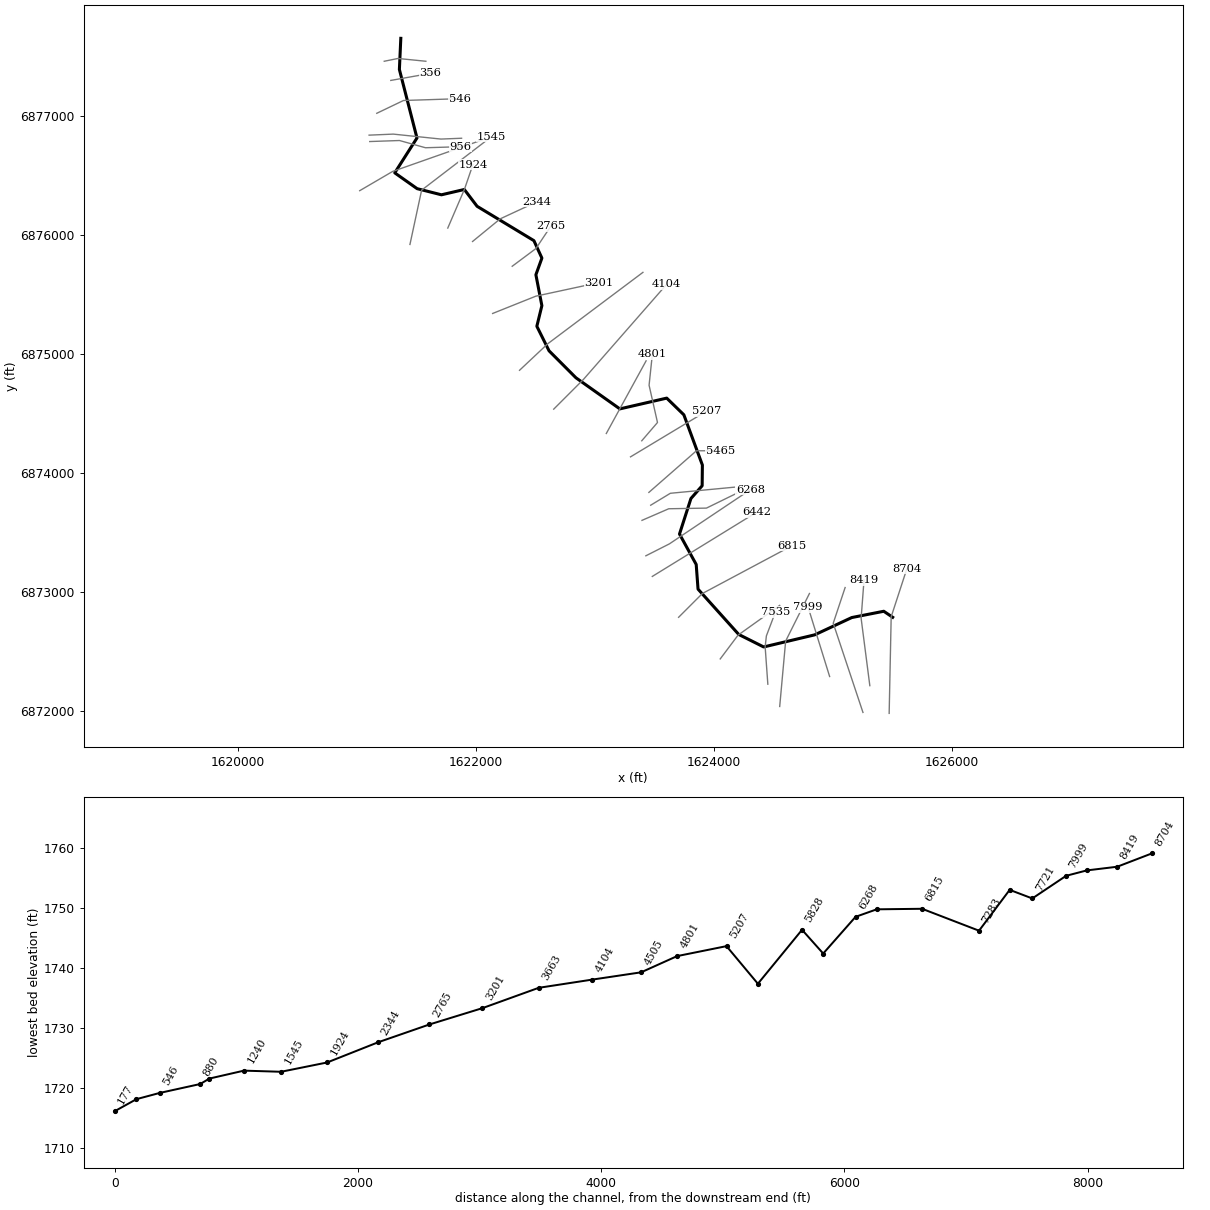
--- Deadman 71.prj (project) ---

Proj Title=Deadman 71 Base Level Engineering
Current Plan=p01
Default Exp/Contr=0.3,0.1
English Units
Geom File=g01
Flow File=f01
Plan File=p01
BEGIN DESCRIPTION:
Deadman 71
END DESCRIPTION:

--- Deadman 71.p01 (plan) ---

Plan Title=Multiple Run
Short Identifier=Multiple
Geom File=g01
Flow File=f01
Subcritical Flow
K Sum by GR= 0
Std Step Tol= 0.01
Critical Tol= 0.01
Num of Std Step Trials= 20
Max Error Tol= 0.3
Flow Tol Ratio= 0.001
Split Flow NTrial= 30
Split Flow Tol= 0.02
Split Flow Ratio= 0.02
Log Output Level= 0
Friction Slope Method= 1
Unsteady Friction Slope Method= 2
Unsteady Bridges Friction Slope Method= 1
Parabolic Critical Depth
Global Vel Dist=  1 , 1 , 1
Global Log Level= 0
CheckData=True
Encroach Param= -1, 0, 0, 0
BEGIN DESCRIPTION:
Multiple Run
END DESCRIPTION:

--- Deadman 71.f01 (steady flow) ---

Flow Title=Multiple
Number of Profiles=7
Profile Names=10-year,25-year,50-year,1pct_min,100-year,1pct_plu,500-year
River Rch & RM= Deadman 71,Reach-1,8704
     197     268     325     196     391     781     576
River Rch & RM= Deadman 71,Reach-1,8419
     279     386     474     290     578    1154     872
Boundary for River Rch & Prof#=Deadman 71,Reach-1,1
Up Type=0
Dn Type=3
Dn Slope=0.007
Boundary for River Rch & Prof#=Deadman 71,Reach-1,2
Up Type=0
Dn Type=3
Dn Slope=0.007
Boundary for River Rch & Prof#=Deadman 71,Reach-1,3
Up Type=0
Dn Type=3
Dn Slope=0.007
Boundary for River Rch & Prof#=Deadman 71,Reach-1,4
Up Type=0
Dn Type=3
Dn Slope=0.007
Boundary for River Rch & Prof#=Deadman 71,Reach-1,5
Up Type=0
Dn Type=3
Dn Slope=0.007
Boundary for River Rch & Prof#=Deadman 71,Reach-1,6
Up Type=0
Dn Type=3
Dn Slope=0.007
Boundary for River Rch & Prof#=Deadman 71,Reach-1,7
Up Type=0
Dn Type=3
Dn Slope=0.007

--- Deadman 71.g01 (geometry) ---

Geom Title=Existing Conditions

River Reach=Deadman 71,Reach-1
Reach XY= 30
      1625505.00      6872788.00      1625429.95      6872838.61
      1625160.94      6872785.74      1624849.03      6872640.33
      1624420.22      6872538.49      1624210.61      6872643.59
      1623868.37      6873024.68      1623852.93      6873232.14
      1623712.53      6873488.01      1623808.56      6873786.53
      1623902.94      6873893.86      1623904.93      6874067.97
      1623749.17      6874490.30      1623605.10      6874630.68
      1623210.97      6874540.14      1622841.79      6874801.63
      1622615.76      6875028.32      1622513.04      6875234.68
      1622555.39      6875408.13      1622505.07      6875667.97
      1622555.60      6875808.05      1622488.37      6875954.71
      1622010.61      6876243.60      1621903.38      6876384.88
      1621710.98      6876340.17      1621506.56      6876391.76
      1621318.40      6876524.64      1621505.29      6876817.82
      1621357.36      6877393.98      1621369.31      6877655.70

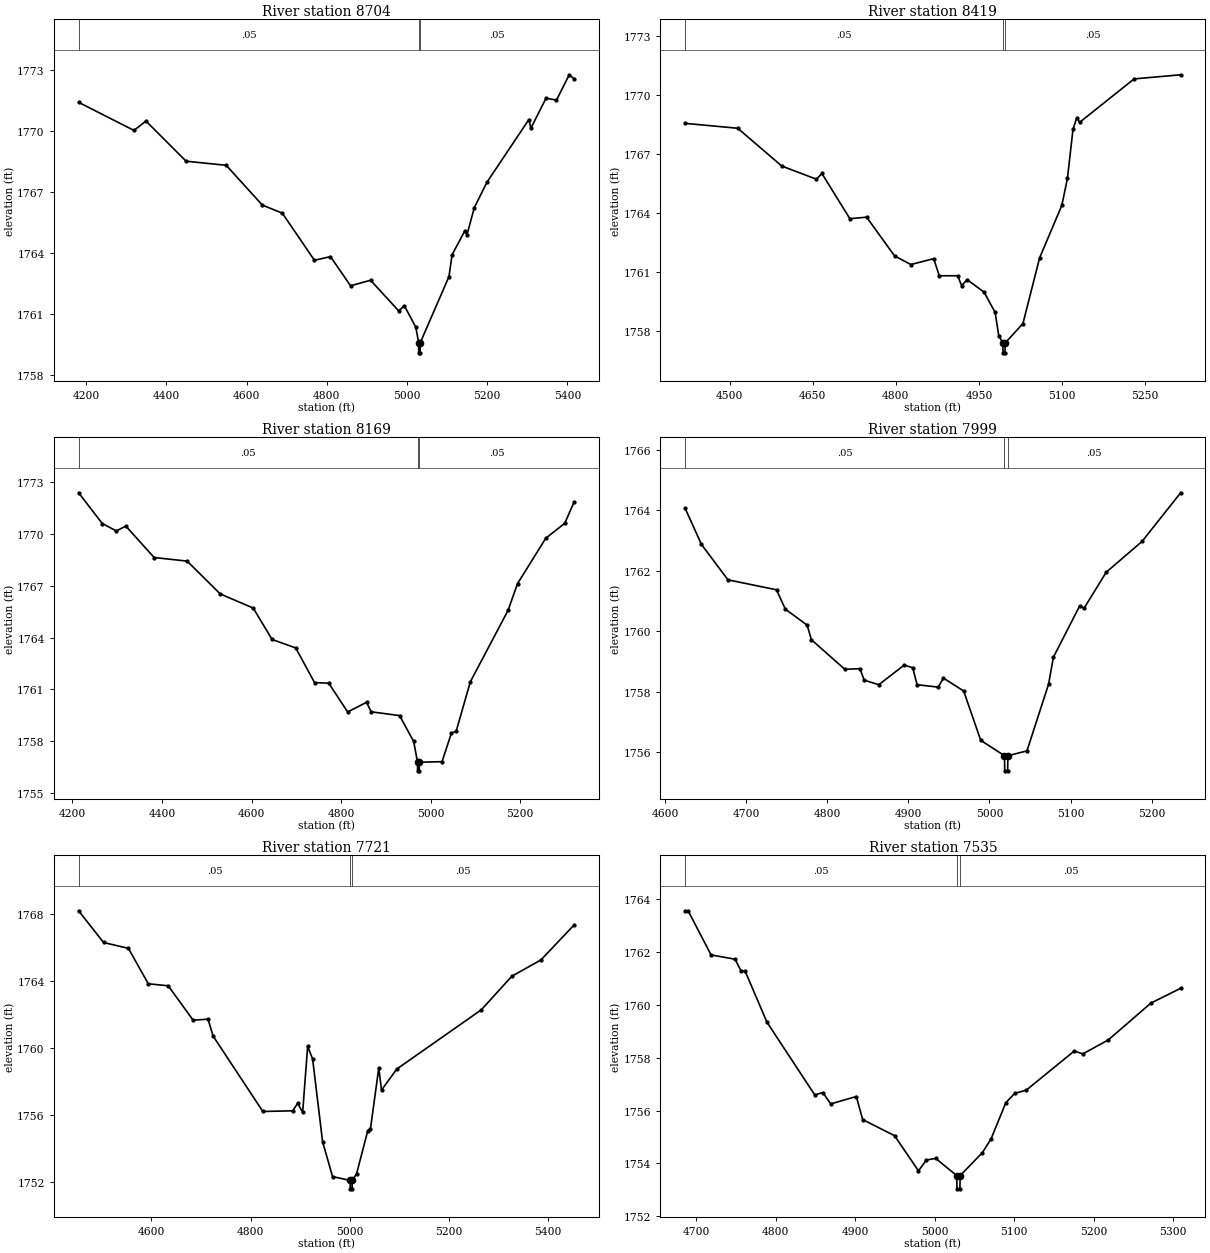
Type RM Length L Ch R = 1,8704,285,285,285
BEGIN DESCRIPTION:
Deadman 71 17.0
END DESCRIPTION:
XS GIS Cut Line= 3
      1625475.30      6871980.08      1625492.27      6872792.15
      1625623.74      6873194.78
#Sta/Elev= 30
  4181.1 1771.40  4319.1 1770.02  4349.1 1770.48  4449.1 1768.51  4549.1 1768.31
  4639.1 1766.36  4689.1 1765.96  4769.2 1763.65  4809.2 1763.83  4859.2 1762.40
  4909.2 1762.67  4979.2 1761.17  4993.4 1761.42  5022.0 1760.37  5029.0 1759.61
  5029.3 1759.11  5032.9 1759.11  5033.1 1759.61  5104.7 1762.85  5112.4 1763.92
  5144.3 1765.10  5149.6 1764.90  5167.8 1766.23  5199.4 1767.48  5303.8 1770.55
  5309.0 1770.13  5346.7 1771.60  5372.8 1771.51  5404.7 1772.75  5416.9 1772.55
#Mann=3,-1,0
  4181.1    0.05       0  5029.0    0.03       0  5033.1    0.05       0
Bank Sta=5029,5033.1
Exp/Cntr=0.3,0.1

Type RM Length L Ch R = 1,8419,250,250,250
BEGIN DESCRIPTION:
Mapping XS 4d119efe
END DESCRIPTION:
XS GIS Cut Line= 3
      1625312.73      6872213.09      1625239.58      6872779.32
      1625263.97      6873101.76
#Sta/Elev= 30
  4419.7 1768.56  4514.7 1768.31  4594.1 1766.39  4656.6 1765.72  4666.6 1766.01
  4717.1 1763.71  4747.3 1763.79  4797.7 1761.82  4827.1 1761.38  4868.3 1761.68
  4878.4 1760.81  4911.5 1760.81  4918.7 1760.31  4928.8 1760.61  4959.1 1759.98
  4979.2 1758.95  4985.8 1757.76  4993.2 1757.39  4993.4 1756.89  4997.0 1756.89
  4997.3 1757.39  5029.4 1758.38  5059.5 1761.72  5099.6 1764.39  5109.7 1765.76
  5119.7 1768.25  5126.7 1768.85  5131.7 1768.61  5230.0 1770.82  5314.0 1771.03
#Mann=3,-1,0
  4419.7    0.05       0  4993.2    0.03       0  4997.3    0.05       0
Bank Sta=4993.2,4997.3
Exp/Cntr=0.3,0.1

Type RM Length L Ch R = 1,8169,170,170,170
BEGIN DESCRIPTION:
Deadman 71 16.0
END DESCRIPTION:
XS GIS Cut Line= 3
      1625254.99      6871988.03      1625005.00      6872738.00
      1625105.01      6873038.03
#Sta/Elev= 30
  4213.7 1772.39  4266.4 1770.61  4298.0 1770.18  4319.1 1770.46  4382.3 1768.64
  4456.1 1768.43  4529.9 1766.53  4603.7 1765.71  4645.8 1763.89  4698.6 1763.40
  4740.7 1761.39  4772.3 1761.36  4814.5 1759.69  4856.7 1760.25  4867.2 1759.70
  4930.5 1759.48  4962.1 1757.98  4970.6 1756.78  4970.8 1756.28  4974.4 1756.28
  4974.7 1756.78  5025.3 1756.81  5046.4 1758.47  5056.9 1758.57  5088.6 1761.44
  5172.9 1765.58  5194.0 1767.13  5257.2 1769.76  5299.4 1770.62  5320.5 1771.86
#Mann=3,-1,0
  4213.7    0.05       0  4970.6    0.05       0  4974.7    0.05       0
Bank Sta=4970.6,4974.7
Exp/Cntr=0.3,0.1

Type RM Length L Ch R = 1,7999,278,278,278
BEGIN DESCRIPTION:
Mapping XS 452175b2
END DESCRIPTION:
XS GIS Cut Line= 2
      1624974.82      6872289.92      1624793.62      6872873.43
#Sta/Elev= 30
  4624.8 1764.07  4645.0 1762.87  4677.6 1761.70  4737.5 1761.37  4748.4 1760.73
  4775.3 1760.20  4780.5 1759.72  4821.7 1758.74  4840.4 1758.76  4845.6 1758.38
  4863.6 1758.23  4895.0 1758.88  4905.5 1758.79  4910.8 1758.23  4936.9 1758.15
  4943.3 1758.45  4968.3 1758.02  4989.3 1756.39  5018.6 1755.88  5018.9 1755.38
  5022.5 1755.38  5022.8 1755.88  5046.3 1756.04  5073.0 1758.25  5078.9 1759.14
  5111.4 1760.84  5116.7 1760.76  5144.0 1761.95  5188.2 1762.97  5235.8 1764.58
#Mann=3,-1,0
  4624.8    0.05       0  5018.6    0.05       0  5022.8    0.05       0
Bank Sta=5018.6,5022.8
Exp/Cntr=0.3,0.1

Type RM Length L Ch R = 1,7721,186,186,186
BEGIN DESCRIPTION:
Deadman 71 15.0
END DESCRIPTION:
XS GIS Cut Line= 3
      1624555.00      6872038.04      1624605.00      6872588.00
      1624804.98      6872987.96
#Sta/Elev= 30
  4453.3 1768.18  4503.5 1766.29  4553.7 1765.94  4593.8 1763.83  4634.0 1763.71
  4684.2 1761.66  4714.3 1761.72  4724.4 1760.72  4824.8 1756.22  4885.0 1756.26
  4895.1 1756.71  4905.1 1756.17  4915.2 1760.10  4925.2 1759.35  4945.3 1754.42
  4965.4 1752.34  5000.9 1752.11  5001.2 1751.61  5004.8 1751.61  5005.1 1752.11
  5013.9 1752.51  5036.3 1755.06  5041.9 1755.19  5058.6 1758.81  5064.2 1757.50
  5095.0 1758.75  5265.5 1762.28  5327.0 1764.28  5385.7 1765.25  5452.7 1767.34
#Mann=3,-1,0
  4453.3    0.05       0  5000.9    0.05       0  5005.1    0.05       0
Bank Sta=5000.9,5005.1
Exp/Cntr=0.3,0.1

Type RM Length L Ch R = 1,7535,252,252,252
BEGIN DESCRIPTION:
Mapping XS 297a9d04
END DESCRIPTION:
XS GIS Cut Line= 4
      1624455.22      6872225.38      1624432.64      6872539.65
      1624443.06      6872631.67      1624519.42      6872832.98
#Sta/Elev= 30
  4686.2 1763.55  4690.0 1763.55  4718.9 1761.88  4749.0 1761.72  4756.5 1761.28
  4761.5 1761.28  4789.1 1759.34  4849.2 1756.59  4859.3 1756.68  4869.3 1756.25
  4901.5 1756.53  4909.4 1755.66  4949.5 1755.05  4979.6 1753.72  4989.6 1754.13
  5001.3 1754.19  5027.7 1753.54  5028.0 1753.04  5031.7 1753.04  5032.0 1753.54
  5060.0 1754.41  5070.9 1754.93  5089.5 1756.30  5100.7 1756.65  5115.1 1756.77
  5175.5 1758.25  5186.2 1758.14  5218.3 1758.67  5271.8 1760.06  5309.2 1760.62
#Mann=3,-1,0
  4686.2    0.05       0  5027.7    0.05       0  5032.0    0.05       0
Bank Sta=5027.7,5032
Exp/Cntr=0.3,0.1

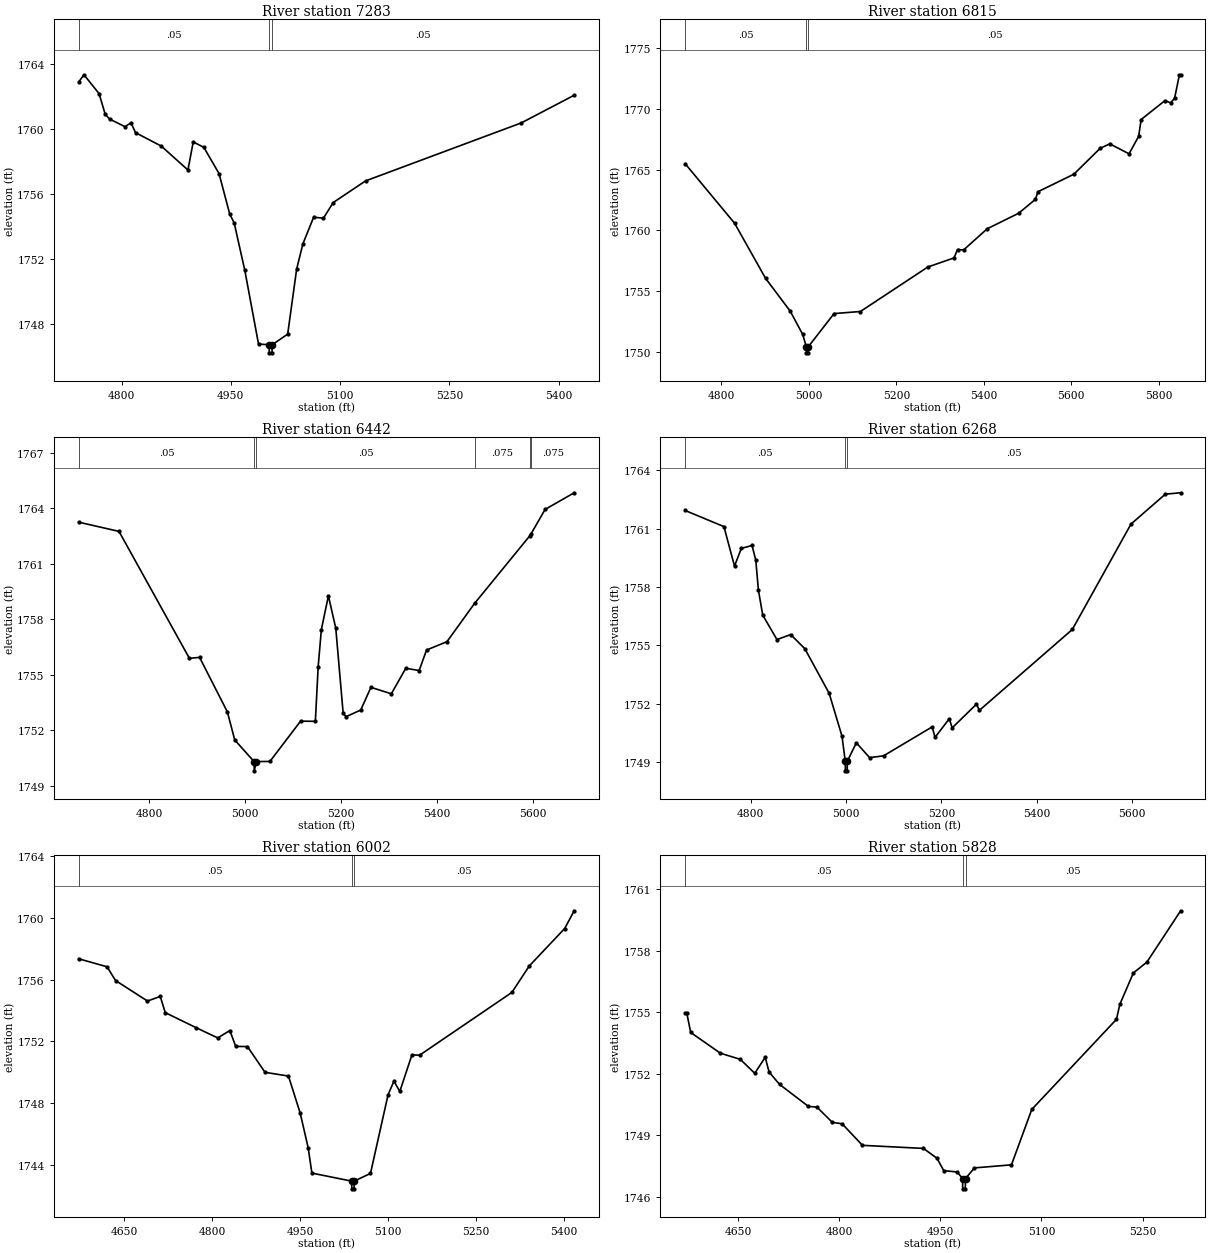
Type RM Length L Ch R = 1,7283,468,468,468
BEGIN DESCRIPTION:
Deadman 71 14.0
END DESCRIPTION:
XS GIS Cut Line= 3
      1624055.00      6872438.00      1624205.00      6872638.00
      1624554.99      6872887.99
#Sta/Elev= 30
  4741.1 1762.90  4748.4 1763.35  4769.2 1762.19  4777.6 1760.91  4783.8 1760.62
  4804.6 1760.16  4813.0 1760.39  4819.2 1759.79  4854.6 1758.96  4891.1 1757.49
  4898.4 1759.22  4913.0 1758.88  4933.8 1757.27  4948.4 1754.79  4954.6 1754.23
  4969.2 1751.31  4988.0 1746.78  5002.5 1746.74  5002.8 1746.24  5006.5 1746.24
  5006.8 1746.74  5028.0 1747.39  5040.3 1751.39  5048.9 1752.95  5063.6 1754.58
  5077.1 1754.53  5090.6 1755.49  5134.9 1756.82  5348.7 1760.39  5421.2 1762.09
#Mann=3,-1,0
  4741.1    0.05       0  5002.5    0.03       0  5006.8    0.05       0
Bank Sta=5002.5,5006.8
Exp/Cntr=0.3,0.1

Type RM Length L Ch R = 1,6815,373,373,373
BEGIN DESCRIPTION:
Deadman 71 13.0
END DESCRIPTION:
XS GIS Cut Line= 3
      1623704.97      6872787.97      1623905.00      6872988.00
      1624655.01      6873388.01
#Sta/Elev= 30
  4717.1 1765.50  4830.3 1760.58  4901.0 1756.04  4957.6 1753.32  4985.8 1751.42
  4994.3 1750.39  4994.6 1749.89  4998.4 1749.89  4998.7 1750.39  5057.7 1753.13
  5117.9 1753.30  5272.0 1756.97  5331.8 1757.72  5340.0 1758.41  5353.8 1758.38
  5408.0 1760.13  5479.9 1761.41  5518.1 1762.56  5523.8 1763.18  5606.0 1764.63
  5666.2 1766.77  5688.1 1767.13  5732.0 1766.31  5754.0 1767.75  5759.7 1769.14
  5814.2 1770.70  5827.3 1770.51  5836.2 1770.90  5847.2 1772.83  5850.0 1772.83
#Mann=3,-1,0
  4717.1    0.05       0  4994.3    0.03       0  4998.7    0.05       0
Bank Sta=4994.3,4998.7
Exp/Cntr=0.3,0.1

Type RM Length L Ch R = 1,6442,174,174,174
BEGIN DESCRIPTION:
Mapping XS 439ef15b
END DESCRIPTION:
XS GIS Cut Line= 2
      1623483.91      6873131.56      1624364.10      6873673.22
#Sta/Elev= 30
  4653.2 1763.26  4737.4 1762.76  4884.2 1755.89  4905.5 1755.94  4963.4 1752.99
  4978.8 1751.47  5019.2 1750.30  5019.5 1749.80  5023.6 1750.30  5052.2 1750.31
  5116.1 1752.49  5146.9 1752.48  5152.8 1755.44  5159.4 1757.44  5174.1 1759.27
  5189.5 1757.52  5204.9 1752.92  5210.7 1752.73  5241.6 1753.09  5262.8 1754.32
  5305.4 1753.97  5335.5 1755.35  5363.4 1755.23  5378.8 1756.34  5421.4 1756.79
  5478.9 1758.86  5593.8 1762.51  5596.6 1762.62  5626.1 1763.95  5686.7 1764.85
#Mann=6,-1,0
  4653.2    0.05       0  5019.2    0.03       0  5023.6    0.05       0
  5478.9   0.075       0  5593.8    0.05       0  5596.6   0.075       0
Bank Sta=5019.2,5023.6
Exp/Cntr=0.3,0.1

Type RM Length L Ch R = 1,6268,266,266,266
BEGIN DESCRIPTION:
Mapping XS 5ade876d
END DESCRIPTION:
XS GIS Cut Line= 3
      1623429.72      6873304.96      1623627.48      6873405.19
      1624307.50      6873860.35
#Sta/Elev= 30
  4662.2 1761.94  4743.7 1761.11  4765.9 1759.08  4780.2 1759.99  4802.7 1760.14
  4810.5 1759.39  4816.1 1757.84  4825.1 1756.56  4855.0 1755.30  4883.9 1755.56
  4913.5 1754.83  4964.5 1752.54  4991.5 1750.33  4998.3 1749.05  4998.6 1748.55
  5002.4 1748.55  5002.7 1749.05  5021.6 1749.99  5049.4 1749.23  5078.6 1749.32
  5180.7 1750.81  5186.7 1750.27  5216.7 1751.23  5222.7 1750.76  5273.7 1751.98
  5279.8 1751.66  5474.9 1755.82  5598.0 1761.24  5670.1 1762.78  5702.2 1762.85
#Mann=3,-1,0
  4662.2    0.05       0  4998.3    0.05       0  5002.7    0.05       0
Bank Sta=4998.3,5002.7
Exp/Cntr=0.3,0.1

Type RM Length L Ch R = 1,6002,174,174,174
BEGIN DESCRIPTION:
Mapping XS a797cf4c
END DESCRIPTION:
XS GIS Cut Line= 4
      1623397.18      6873602.98      1623622.06      6873700.52
      1623939.06      6873705.94      1624193.73      6873830.56
#Sta/Elev= 30
  4571.8 1757.35  4620.3 1756.83  4634.8 1755.94  4689.3 1754.61  4711.1 1754.91
  4719.6 1753.86  4772.0 1752.89  4809.2 1752.22  4829.9 1752.70  4839.9 1751.67
  4859.9 1751.66  4889.9 1749.99  4929.9 1749.75  4949.9 1747.35  4963.5 1745.11
  4969.9 1743.46  5037.7 1742.94  5038.0 1742.44  5041.8 1742.44  5042.1 1742.94
  5069.9 1743.44  5099.9 1748.54  5109.9 1749.42  5119.9 1748.75  5140.6 1751.12
  5153.7 1751.10  5311.2 1755.17  5341.0 1756.89  5401.3 1759.31  5417.5 1760.46
#Mann=3,-1,0
  4571.8    0.05       0  5037.7    0.05       0  5042.1    0.05       0
Bank Sta=5037.7,5042.1
Exp/Cntr=0.3,0.1

Type RM Length L Ch R = 1,5828,363,363,363
BEGIN DESCRIPTION:
Mapping XS eb3e6238
END DESCRIPTION:
XS GIS Cut Line= 3
      1623470.30      6873730.30      1623635.61      6873830.57
      1624174.81      6873882.05
#Sta/Elev= 30
  4571.5 1754.94  4574.1 1754.94  4579.8 1754.01  4623.8 1753.00  4653.4 1752.70
  4674.8 1752.02  4690.3 1752.80  4696.1 1752.08  4711.6 1751.48  4754.3 1750.41
  4767.1 1750.37  4789.9 1749.63  4804.4 1749.56  4834.6 1748.51  4925.0 1748.36
  4945.1 1747.88  4955.1 1747.28  4975.2 1747.21  4983.0 1746.89  4983.3 1746.39
  4987.1 1746.39  4987.4 1746.89  5000.6 1747.41  5055.6 1747.56  5085.7 1750.26
  5211.3 1754.65  5216.3 1755.38  5236.4 1756.91  5256.5 1757.44  5306.5 1759.94
#Mann=3,-1,0
  4571.5    0.05       0  4983.0    0.05       0  4987.4    0.05       0
Bank Sta=4983,4987.4
Exp/Cntr=0.3,0.1

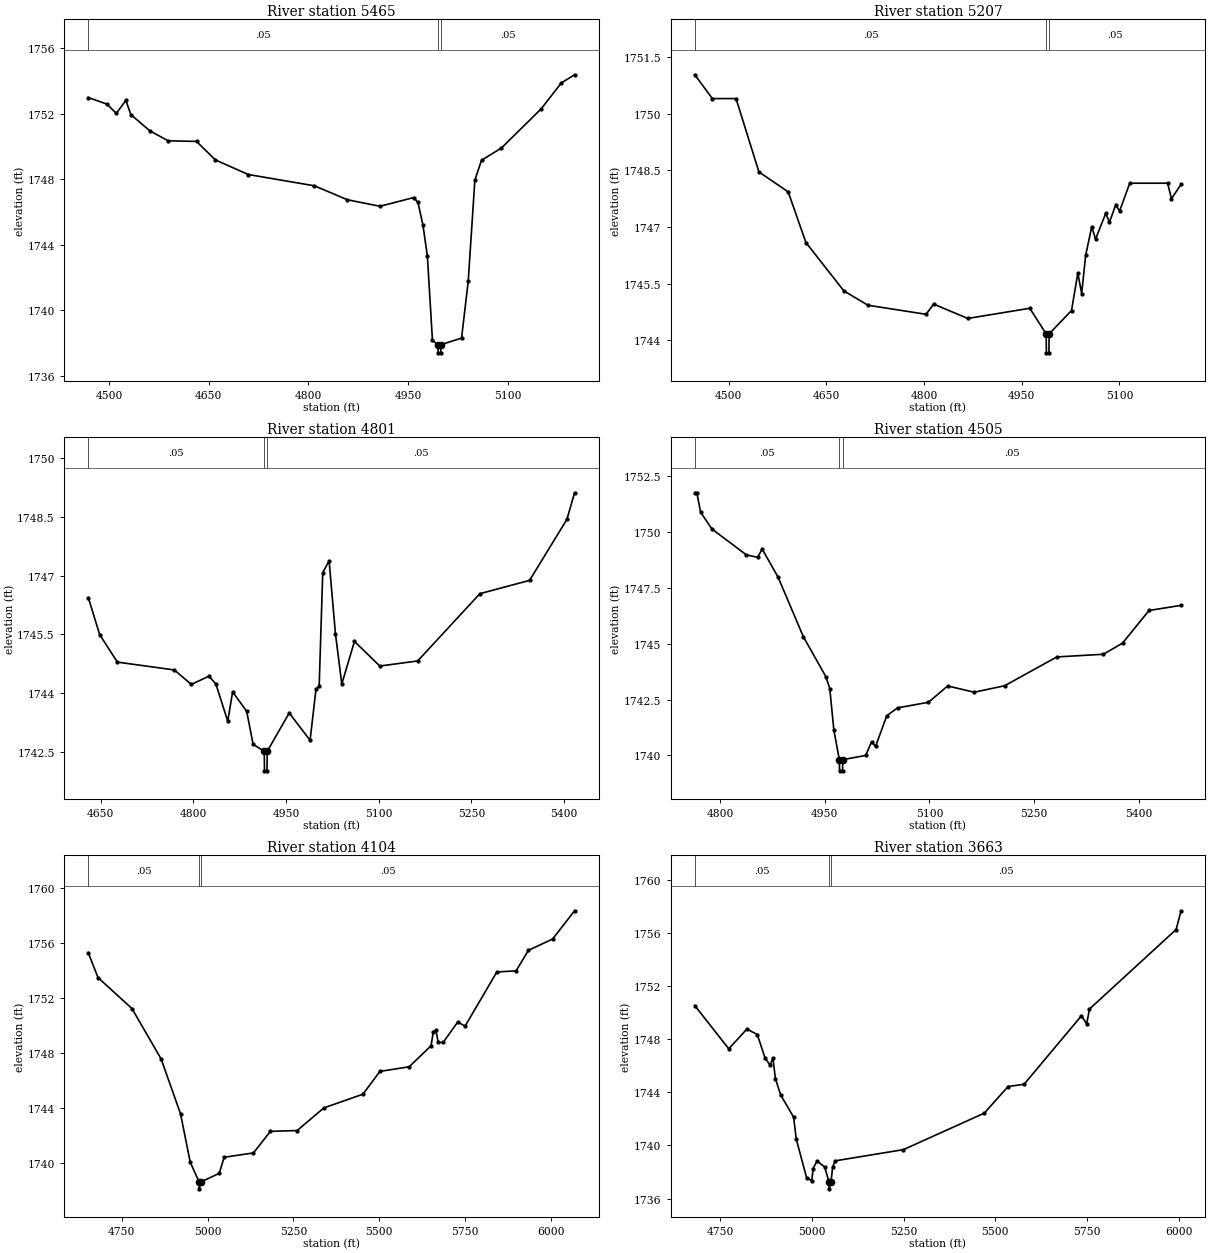
Type RM Length L Ch R = 1,5465,258,258,258
BEGIN DESCRIPTION:
Deadman 71 10.0
END DESCRIPTION:
XS GIS Cut Line= 3
      1623455.01      6873838.01      1623855.00      6874188.00
      1624055.01      6874188.00
#Sta/Elev= 30
  4468.8 1753.00  4496.8 1752.60  4511.0 1752.03  4525.3 1752.83  4532.8 1751.96
  4561.3 1750.97  4588.8 1750.36  4631.6 1750.32  4660.0 1749.19  4709.4 1748.30
  4809.0 1747.61  4858.4 1746.76  4907.7 1746.36  4958.1 1746.89  4964.7 1746.60
  4972.3 1745.19  4978.9 1743.31  4986.5 1738.17  4994.7 1737.91  4995.0 1737.41
  4998.9 1737.41  4999.2 1737.91  5030.3 1738.31  5040.3 1741.78  5050.3 1747.95
  5060.3 1749.17  5090.3 1749.92  5150.3 1752.32  5180.3 1753.89  5200.3 1754.39
#Mann=3,-1,0
  4468.8    0.05       0  4994.7    0.05       0  4999.2    0.05       0
Bank Sta=4994.7,4999.2
Exp/Cntr=0.3,0.1

Type RM Length L Ch R = 1,5207,406,406,406
BEGIN DESCRIPTION:
Mapping XS 791785a0
END DESCRIPTION:
XS GIS Cut Line= 2
      1623300.72      6874136.89      1623940.64      6874521.88
#Sta/Elev= 30
  4447.9 1751.03  4474.8 1750.40  4511.2 1750.40  4546.3 1748.46  4591.3 1747.93
  4618.5 1746.59  4676.8 1745.31  4713.7 1744.93  4803.0 1744.69  4814.7 1744.96
  4867.1 1744.58  4962.3 1744.85  4987.5 1744.17  4987.8 1743.67  4991.7 1743.67
  4992.0 1744.17  5026.4 1744.79  5036.1 1745.78  5042.0 1745.24  5048.1 1746.25
  5057.5 1747.01  5063.3 1746.68  5078.9 1747.36  5084.7 1747.13  5094.4 1747.59
  5100.2 1747.42  5115.8 1748.16  5174.0 1748.16  5179.9 1747.75  5194.7 1748.13
#Mann=3,-1,0
  4447.9    0.05       0  4987.5    0.05       0  4992.0    0.05       0
Bank Sta=4987.5,4992
Exp/Cntr=0.3,0.1

Type RM Length L Ch R = 1,4801,296,296,296
BEGIN DESCRIPTION:
Mapping XS 5d91c9a5
END DESCRIPTION:
XS GIS Cut Line= 4
      1623395.27      6874272.00      1623527.42      6874425.67
      1623456.74      6874739.12      1623484.40      6875000.36
#Sta/Elev= 30
  4630.1 1746.44  4648.6 1745.49  4677.2 1744.79  4769.3 1744.59  4796.8 1744.22
  4825.3 1744.43  4836.5 1744.23  4855.7 1743.28  4863.6 1744.03  4886.4 1743.53
  4896.7 1742.69  4914.8 1742.51  4915.1 1742.01  4919.2 1742.01  4919.6 1742.51
  4955.2 1743.49  4988.9 1742.79  4998.5 1744.10  5003.6 1744.17  5009.4 1747.08
  5019.7 1747.38  5029.9 1745.52  5040.2 1744.23  5060.7 1745.32  5101.7 1744.69
  5163.0 1744.82  5263.6 1746.54  5344.0 1746.88  5404.4 1748.44  5416.8 1749.12
#Mann=3,-1,0
  4630.1    0.05       0  4914.8    0.05       0  4919.6    0.05       0
Bank Sta=4914.8,4919.6
Exp/Cntr=0.3,0.1

Type RM Length L Ch R = 1,4505,401,401,401
BEGIN DESCRIPTION:
Mapping XS 78f95f20
END DESCRIPTION:
XS GIS Cut Line= 2
      1623097.20      6874333.49      1623431.60      6874944.01
#Sta/Elev= 30
  4764.1 1751.76  4767.0 1751.76  4772.4 1750.89  4788.5 1750.14  4837.9 1748.98
  4854.0 1748.87  4860.5 1749.24  4883.3 1747.98  4919.4 1745.32  4951.6 1743.53
  4957.3 1742.99  4963.1 1741.14  4971.0 1739.81  4971.3 1739.31  4975.5 1739.31
  4975.9 1739.81  5008.7 1740.00  5017.1 1740.61  5022.8 1740.40  5038.9 1741.78
  5054.3 1742.13  5098.6 1742.38  5126.1 1743.11  5164.0 1742.83  5207.6 1743.12
  5282.3 1744.41  5348.9 1744.53  5376.4 1745.03  5414.3 1746.49  5460.2 1746.72
#Mann=3,-1,0
  4764.1    0.05       0  4971.0    0.05       0  4975.9    0.05       0
Bank Sta=4971,4975.9
Exp/Cntr=0.3,0.1

Type RM Length L Ch R = 1,4104,441,441,441
BEGIN DESCRIPTION:
Deadman 71 7.0
END DESCRIPTION:
XS GIS Cut Line= 3
      1622655.01      6874538.01      1622905.00      6874788.00
      1623605.03      6875588.04
#Sta/Elev= 30
  4652.3 1755.31  4680.6 1753.50  4779.6 1751.24  4864.4 1747.57  4921.0 1743.57
  4949.3 1740.04  4975.1 1738.60  4975.5 1738.10  4980.1 1738.60  5033.8 1739.23
  5048.1 1740.40  5133.5 1740.72  5182.8 1742.29  5260.7 1742.35  5338.5 1744.00
  5452.4 1745.00  5501.8 1746.66  5587.2 1747.00  5650.8 1748.53  5657.4 1749.55
  5665.0 1749.67  5671.6 1748.77  5685.9 1748.77  5728.6 1750.26  5749.9 1749.96
  5842.5 1753.91  5898.5 1753.99  5934.6 1755.49  6004.8 1756.31  6068.9 1758.37
#Mann=3,-1,0
  4652.3    0.05       0  4975.1    0.05       0  4980.1    0.05       0
Bank Sta=4975.1,4980.1
Exp/Cntr=0.3,0.1

Type RM Length L Ch R = 1,3663,462,462,462
BEGIN DESCRIPTION:
Deadman 71 6.0
END DESCRIPTION:
XS GIS Cut Line= 3
      1622367.57      6874864.67      1622605.00      6875088.00
      1623405.04      6875688.03
#Sta/Elev= 30
  4680.7 1750.52  4773.3 1747.27  4822.8 1748.76  4851.1 1748.34  4872.1 1746.59
  4886.3 1746.02  4893.6 1746.60  4900.4 1745.03  4914.6 1743.81  4950.2 1742.12
  4957.1 1740.50  4985.4 1737.57  4999.6 1737.34  5003.2 1738.25  5013.9 1738.83
  5034.8 1738.37  5046.9 1737.23  5047.2 1736.73  5051.9 1737.23  5056.7 1738.39
  5063.9 1738.84  5249.4 1739.68  5470.2 1742.43  5534.8 1744.43  5578.5 1744.60
  5734.8 1749.75  5749.4 1749.15  5756.7 1750.26  5993.1 1756.25  6006.7 1757.66
#Mann=3,-1,0
  4680.7    0.05       0  5046.9    0.05       0  5051.9    0.05       0
Bank Sta=5046.9,5051.9
Exp/Cntr=0.3,0.1

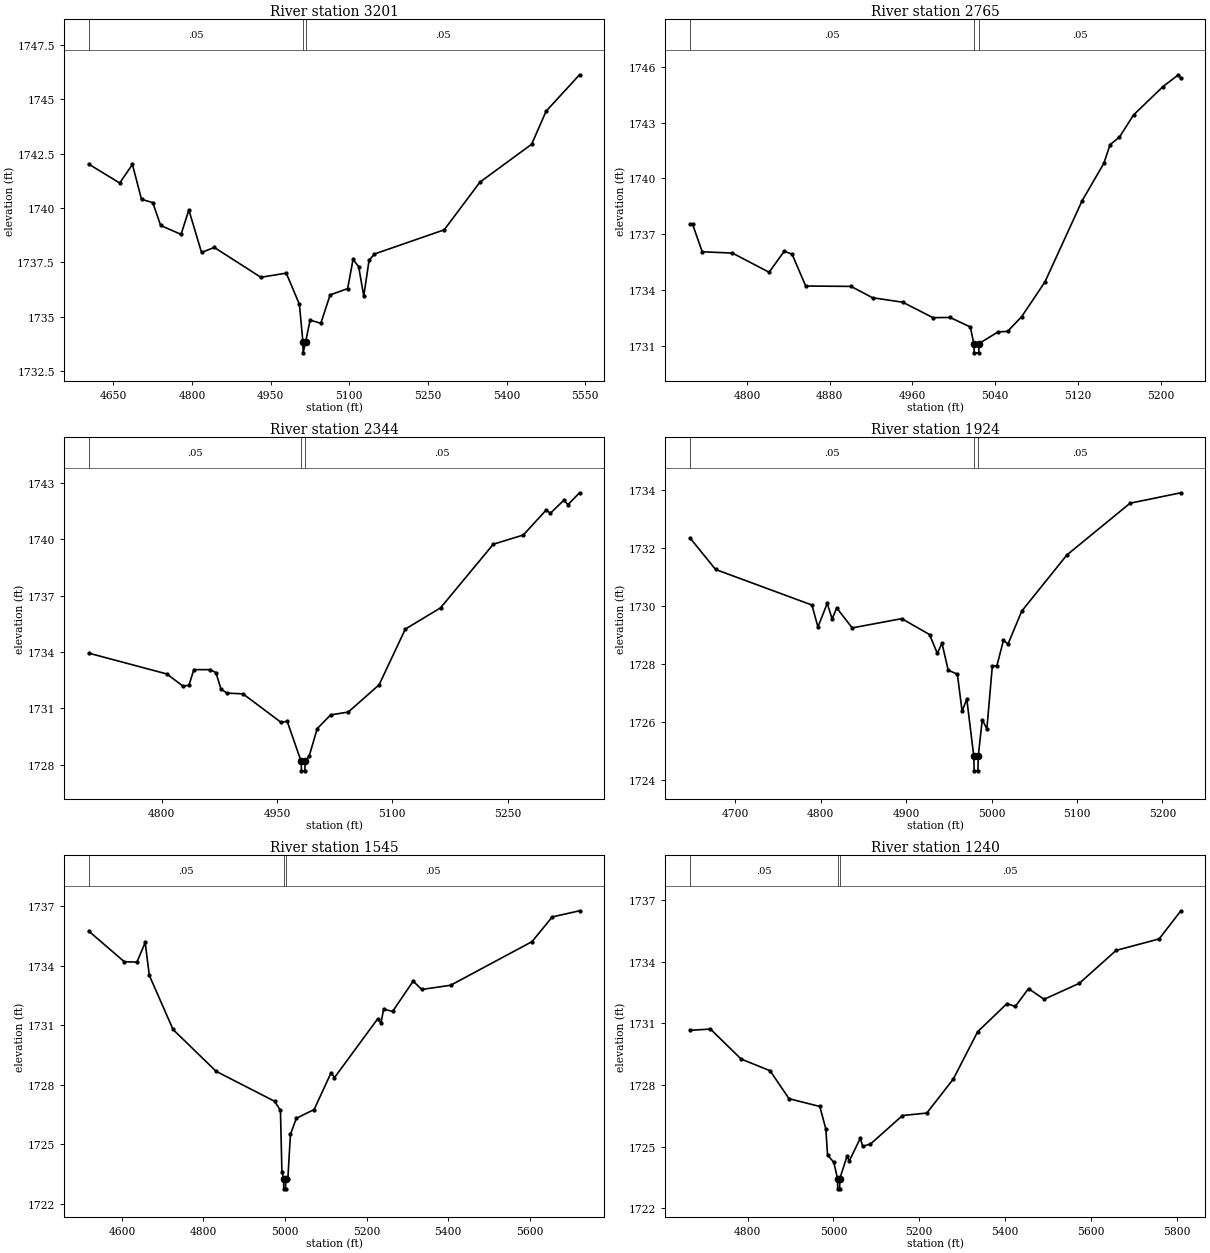
Type RM Length L Ch R = 1,3201,436,436,436
BEGIN DESCRIPTION:
Deadman 71 5.0
END DESCRIPTION:
XS GIS Cut Line= 3
      1622141.43      6875342.42      1622505.00      6875488.00
      1623037.26      6875602.64
#Sta/Elev= 30
  4603.1 1742.02  4662.3 1741.15  4686.6 1742.00  4703.9 1740.40  4725.4 1740.25
  4740.4 1739.20  4779.3 1738.79  4794.2 1739.91  4818.4 1737.96  4842.7 1738.19
  4931.5 1736.82  4979.9 1737.01  5005.0 1735.58  5011.7 1733.85  5012.1 1733.35
  5016.8 1733.85  5025.4 1734.85  5045.9 1734.71  5063.6 1736.01  5097.0 1736.30
  5107.3 1737.64  5118.0 1737.31  5127.7 1735.96  5137.9 1737.60  5148.2 1737.89
  5281.2 1739.00  5349.3 1741.19  5447.9 1742.93  5475.5 1744.45  5539.2 1746.12
#Mann=3,-1,0
  4603.1    0.05       0  5011.7    0.05       0  5016.8    0.05       0
Bank Sta=5011.7,5016.8
Exp/Cntr=0.3,0.1

Type RM Length L Ch R = 1,2765,421,421,421
BEGIN DESCRIPTION:
Deadman 71 4.0
END DESCRIPTION:
XS GIS Cut Line= 3
      1622305.94      6875739.33      1622505.00      6875888.00
      1622630.55      6876076.10
#Sta/Elev= 30
  4745.0 1737.54  4747.5 1737.54  4756.8 1736.06  4786.0 1735.99  4821.5 1734.96
  4836.1 1736.09  4843.7 1735.93  4856.9 1734.22  4900.7 1734.20  4921.5 1733.59
  4950.7 1733.35  4979.9 1732.52  4996.5 1732.53  5016.0 1732.02  5019.4 1731.13
  5019.8 1730.63  5024.1 1730.63  5024.5 1731.13  5043.0 1731.76  5052.0 1731.78
  5065.6 1732.57  5088.1 1734.43  5124.1 1738.80  5145.1 1740.81  5151.2 1741.82
  5160.2 1742.22  5173.8 1743.41  5202.2 1744.93  5217.2 1745.57  5219.6 1745.39
#Mann=3,-1,0
  4745.0    0.05       0  5019.4    0.05       0  5024.5    0.05       0
Bank Sta=5019.4,5024.5
Exp/Cntr=0.3,0.1

Type RM Length L Ch R = 1,2344,420,420,420
BEGIN DESCRIPTION:
Deadman 71 3.0
END DESCRIPTION:
XS GIS Cut Line= 3
      1621972.58      6875947.64      1622205.00      6876138.00
      1622511.29      6876280.41
#Sta/Elev= 30
  4705.2 1733.94  4806.8 1732.83  4827.6 1732.19  4835.5 1732.22  4842.0 1733.06
  4863.4 1733.06  4870.7 1732.90  4877.2 1732.03  4885.0 1731.81  4905.9 1731.77
  4955.4 1730.25  4963.3 1730.31  4981.5 1728.17  4981.9 1727.67  4986.3 1727.67
  4986.7 1728.17  4992.0 1728.47  5002.4 1729.92  5019.8 1730.65  5042.7 1730.80
  5082.8 1732.25  5116.9 1735.22  5162.7 1736.35  5231.3 1739.74  5270.3 1740.23
  5300.0 1741.56  5305.5 1741.39  5322.9 1742.08  5328.4 1741.85  5343.4 1742.48
#Mann=3,-1,0
  4705.2    0.05       0  4981.5    0.05       0  4986.7    0.05       0
Bank Sta=4981.5,4986.7
Exp/Cntr=0.3,0.1

Type RM Length L Ch R = 1,1924,379,379,379
BEGIN DESCRIPTION:
Deadman 71 2.0
END DESCRIPTION:
XS GIS Cut Line= 3
      1621764.24      6876060.49      1621905.00      6876388.00
      1621975.68      6876594.15
#Sta/Elev= 30
  4647.1 1732.35  4677.0 1731.26  4789.8 1730.03  4796.8 1729.27  4807.7 1730.09
  4813.4 1729.55  4818.8 1729.93  4836.9 1729.24  4894.9 1729.56  4927.4 1729.01
  4936.5 1728.36  4942.0 1728.71  4949.2 1727.78  4960.0 1727.64  4965.5 1726.36
  4971.0 1726.78  4979.2 1724.80  4979.6 1724.30  4984.0 1724.30  4984.4 1724.80
  4989.1 1726.07  4994.5 1725.75  5000.9 1727.93  5006.2 1727.93  5013.9 1728.81
  5019.2 1728.68  5035.3 1729.82  5088.1 1731.76  5162.1 1733.55  5221.5 1733.91
#Mann=3,-1,0
  4647.1    0.05       0  4979.2    0.05       0  4984.4    0.05       0
Bank Sta=4979.2,4984.4
Exp/Cntr=0.3,0.1

Type RM Length L Ch R = 1,1545,305,305,305
BEGIN DESCRIPTION:
Mapping XS c2a4c687
END DESCRIPTION:
XS GIS Cut Line= 3
      1621446.12      6875922.62      1621544.23      6876379.04
      1622128.67      6876826.97
#Sta/Elev= 30
  4518.5 1735.76  4605.8 1734.21  4636.9 1734.19  4657.0 1735.18  4667.2 1733.52
  4725.4 1730.79  4830.9 1728.68  4974.1 1727.17  4988.6 1726.71  4992.2 1723.62
  4996.3 1723.25  4996.7 1722.75  5001.2 1722.75  5001.6 1723.25  5006.8 1723.27
  5013.1 1725.50  5027.6 1726.31  5071.1 1726.75  5112.8 1728.61  5121.0 1728.36
  5227.0 1731.33  5235.2 1731.12  5241.5 1731.82  5263.5 1731.70  5313.9 1733.23
  5334.9 1732.81  5405.6 1733.02  5605.0 1735.22  5654.9 1736.47  5721.7 1736.78
#Mann=3,-1,0
  4518.5    0.05       0  4996.3    0.05       0  5001.6    0.05       0
Bank Sta=4996.3,5001.6
Exp/Cntr=0.3,0.1

Type RM Length L Ch R = 1,1240,284,284,284
BEGIN DESCRIPTION:
Mapping XS a7b2eeef
END DESCRIPTION:
XS GIS Cut Line= 3
      1621023.80      6876374.78      1621301.07      6876536.88
      1622077.49      6876809.90
#Sta/Elev= 30
  4665.5 1730.66  4713.2 1730.72  4784.7 1729.26  4852.2 1728.69  4896.3 1727.33
  4968.1 1726.95  4982.2 1725.85  4986.1 1724.58  5000.6 1724.24  5009.4 1723.44
  5009.8 1722.94  5014.3 1722.94  5014.7 1723.44  5031.6 1724.53  5036.9 1724.30
  5062.6 1725.41  5067.9 1725.01  5086.2 1725.12  5160.8 1726.51  5217.5 1726.63
  5279.4 1728.29  5336.0 1730.59  5404.3 1731.96  5423.7 1731.82  5454.6 1732.69
  5490.9 1732.17  5573.2 1732.95  5658.7 1734.55  5759.1 1735.11  5809.7 1736.48
#Mann=3,-1,0
  4665.5    0.05       0  5009.4    0.05       0  5014.7    0.05       0
Bank Sta=5009.4,5014.7
Exp/Cntr=0.3,0.1

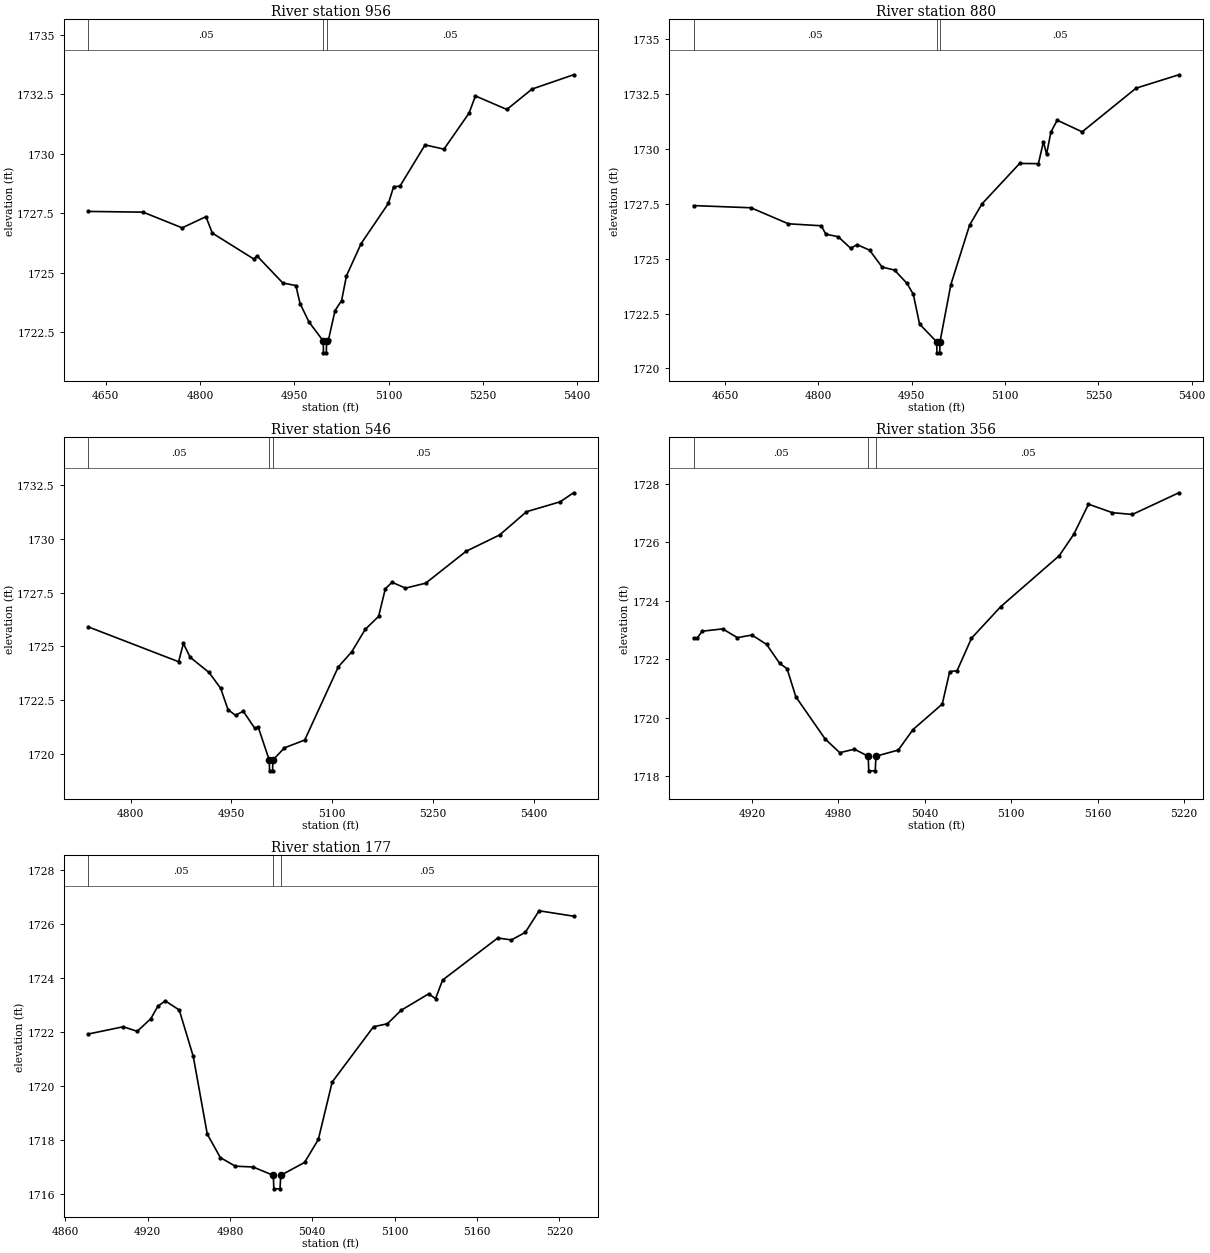
Type RM Length L Ch R = 1,956,76,76,76
BEGIN DESCRIPTION:
Mapping XS 0ced9033
END DESCRIPTION:
XS GIS Cut Line= 4
      1621107.97      6876787.92      1621357.99      6876796.60
      1621576.74      6876735.84      1621870.91      6876744.49
#Sta/Elev= 30
  4622.5 1727.57  4709.6 1727.54  4771.8 1726.88  4809.6 1727.35  4819.7 1726.66
  4885.6 1725.57  4890.8 1725.70  4931.8 1724.56  4952.6 1724.45  4959.3 1723.69
  4973.4 1722.92  4996.1 1722.12  4996.5 1721.62  5001.0 1721.62  5001.4 1722.12
  5004.5 1722.18  5014.9 1723.40  5025.3 1723.82  5033.0 1724.86  5056.4 1726.22
  5099.7 1727.91  5108.0 1728.61  5118.0 1728.63  5158.0 1730.37  5188.0 1730.19
  5228.0 1731.71  5238.0 1732.43  5288.0 1731.86  5328.1 1732.72  5394.0 1733.32
#Mann=3,-1,0
  4622.5    0.05       0  4996.1    0.03       0  5001.4    0.05       0
Bank Sta=4996.1,5001.4
Exp/Cntr=0.3,0.1

Type RM Length L Ch R = 1,880,334,334,334
BEGIN DESCRIPTION:
Mapping XS 1ee2741c
END DESCRIPTION:
XS GIS Cut Line= 4
      1621102.74      6876841.74      1621305.91      6876850.42
      1621706.95      6876808.75      1621880.26      6876815.68
#Sta/Elev= 30
  4599.3 1727.42  4691.6 1727.32  4751.7 1726.59  4804.7 1726.50  4811.8 1726.12
  4831.9 1726.00  4852.0 1725.47  4862.1 1725.64  4882.2 1725.39  4902.3 1724.62
  4922.4 1724.48  4942.5 1723.87  4952.5 1723.38  4962.6 1722.02  4990.1 1721.21
  4990.5 1720.71  4995.0 1720.71  4995.4 1721.21  5012.9 1723.82  5043.0 1726.53
  5063.0 1727.50  5123.5 1729.34  5153.6 1729.33  5161.7 1730.33  5166.7 1729.76
  5173.7 1730.77  5183.8 1731.31  5223.9 1730.78  5310.6 1732.77  5379.3 1733.38
#Mann=3,-1,0
  4599.3    0.05       0  4990.1    0.03       0  4995.4    0.05       0
Bank Sta=4990.1,4995.4
Exp/Cntr=0.3,0.1

Type RM Length L Ch R = 1,546,190,190,190
BEGIN DESCRIPTION:
Mapping XS cdd4b887
END DESCRIPTION:
XS GIS Cut Line= 3
      1621167.33      6877025.49      1621391.64      6877133.03
      1621864.93      6877148.40
#Sta/Elev= 30
  4736.8 1725.91  4871.3 1724.29  4878.4 1725.14  4888.4 1724.50  4916.6 1723.79
  4933.8 1723.06  4944.9 1722.06  4956.0 1721.80  4967.5 1721.99  4984.6 1721.20
  4989.7 1721.26  5006.2 1719.72  5006.7 1719.22  5011.2 1719.22  5011.6 1719.72
  5028.9 1720.29  5059.0 1720.65  5109.0 1724.05  5129.0 1724.75  5149.0 1725.79
  5169.0 1726.40  5179.0 1727.68  5189.0 1727.98  5209.0 1727.71  5239.1 1727.94
  5299.1 1729.42  5349.1 1730.18  5389.1 1731.26  5439.2 1731.72  5459.1 1732.14
#Mann=3,-1,0
  4736.8    0.05       0  5006.2    0.03       0  5011.6    0.05       0
Bank Sta=5006.2,5011.6
Exp/Cntr=0.3,0.1

Type RM Length L Ch R = 1,356,179,179,179
BEGIN DESCRIPTION:
Mapping XS f11c2f10
END DESCRIPTION:
XS GIS Cut Line= 2
      1621285.10      6877301.81      1621616.69      6877360.84
#Sta/Elev= 30
  4879.5 1722.72  4882.0 1722.72  4885.4 1722.96  4899.7 1723.04  4909.9 1722.74
  4920.0 1722.83  4930.2 1722.51  4939.3 1721.86  4944.4 1721.68  4950.5 1720.72
  4970.8 1719.28  4981.0 1718.81  4991.1 1718.93  5000.7 1718.69  5001.1 1718.19
  5005.6 1718.19  5006.1 1718.69  5021.6 1718.90  5031.8 1719.60  5052.1 1720.47
  5057.3 1721.58  5062.4 1721.61  5072.4 1722.72  5092.7 1723.80  5133.3 1725.54
  5143.5 1726.28  5153.6 1727.30  5170.2 1727.01  5184.1 1726.95  5216.3 1727.69
#Mann=3,-1,0
  4879.5    0.05       0  5000.7    0.05       0  5006.1    0.05       0
Bank Sta=5000.7,5006.1
Exp/Cntr=0.3,0.1

Type RM Length L Ch R = 1,177,0,0,0
BEGIN DESCRIPTION:
Deadman 71 1.0
END DESCRIPTION:
XS GIS Cut Line= 3
      1621229.99      6877463.00      1621345.54      6877486.43
      1621579.97      6877463.00
#Sta/Elev= 30
  4876.8 1721.92  4902.3 1722.19  4912.5 1722.02  4922.4 1722.49  4927.5 1722.95
  4932.9 1723.15  4943.1 1722.81  4953.3 1721.09  4963.5 1718.21  4973.0 1717.34
  4983.9 1717.02  4996.9 1716.99  5011.6 1716.68  5012.0 1716.18  5016.5 1716.18
  5017.0 1716.68  5034.4 1717.16  5044.4 1718.01  5054.5 1720.14  5084.6 1722.19
  5094.7 1722.30  5104.7 1722.80  5124.8 1723.41  5129.8 1723.23  5134.9 1723.92
  5175.1 1725.48  5185.1 1725.41  5195.2 1725.69  5205.2 1726.49  5230.3 1726.29
#Mann=3,-1,0
  4876.8    0.05       0  5011.6    0.05       0  5017.0    0.05       0
Bank Sta=5011.6,5017
Exp/Cntr=0.3,0.1

Chan Stop Cuts=-1