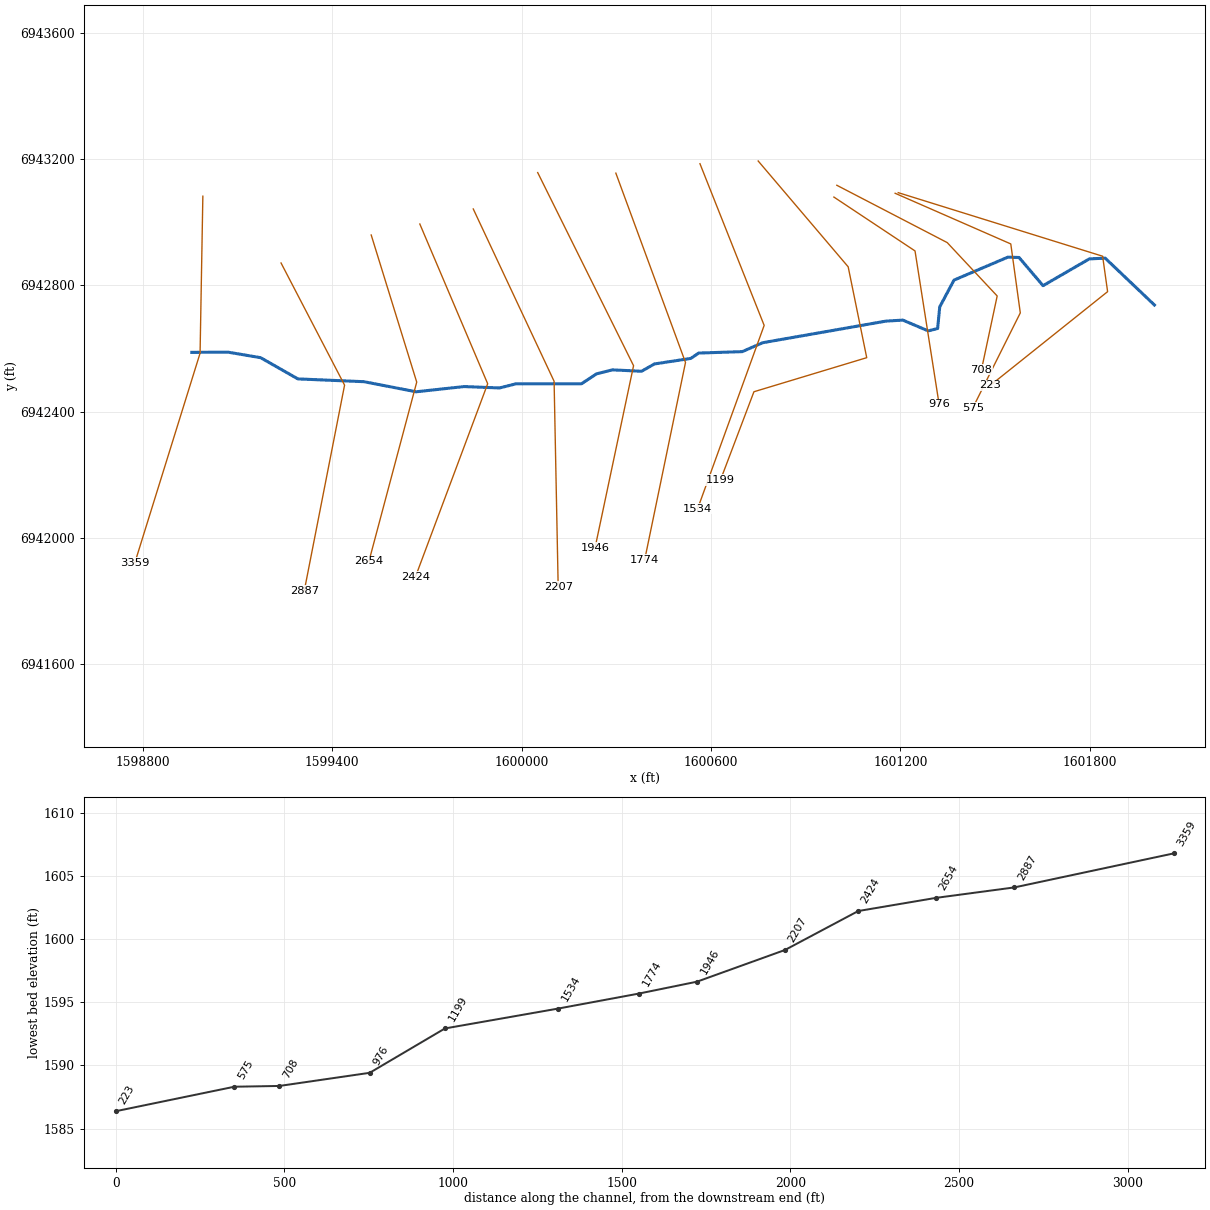
--- Deadman 75.prj (project) ---

Proj Title=Deadman 75 Base Level Engineering
Current Plan=p01
Default Exp/Contr=0.3,0.1
English Units
Geom File=g01
Flow File=f01
Plan File=p01
Y Axis Title=Elevation
X Axis Title(PF)=Main Channel Distance
X Axis Title(XS)=Station
BEGIN DESCRIPTION:
Deadman 75
END DESCRIPTION:
DSS Export Rating Curves= 0
DSS Export Rating Curve Sorted= 0
DSS Export Volume Flow Curves= 0
DXF OffsetX= 0
DXF OffsetY= 0
DXF ScaleX= 1
DXF ScaleY= 10

--- Deadman 75.p01 (plan) ---

Plan Title=Multiple Run
Short Identifier=Multiple
Geom File=g01
Flow File=f01
Subcritical Flow
K Sum by GR= 0
Std Step Tol= 0.01
Critical Tol= 0.01
Num of Std Step Trials= 20
Max Error Tol= 0.3
Flow Tol Ratio= 0.001
Split Flow NTrial= 30
Split Flow Tol= 0.02
Split Flow Ratio= 0.02
Log Output Level= 0
Friction Slope Method= 1
Unsteady Friction Slope Method= 2
Unsteady Bridges Friction Slope Method= 1
Parabolic Critical Depth
Global Vel Dist=  1 , 1 , 1
Global Log Level= 0
CheckData=True
Encroach Param= -1, 0, 0, 0
BEGIN DESCRIPTION:
Multiple Run
END DESCRIPTION:

--- Deadman 75.f01 (steady flow) ---

Flow Title=Multiple
Number of Profiles=7
Profile Names=10-year,25-year,50-year,1pct_min,100-year,1pct_plu,500-year
River Rch & RM= Deadman 75,Reach-1,3359
     292     409     508     315     628    1252     969
Boundary for River Rch & Prof#=Deadman 75,Reach-1,1
Up Type=0
Dn Type=3
Dn Slope=0.009
Boundary for River Rch & Prof#=Deadman 75,Reach-1,2
Up Type=0
Dn Type=3
Dn Slope=0.009
Boundary for River Rch & Prof#=Deadman 75,Reach-1,3
Up Type=0
Dn Type=3
Dn Slope=0.009
Boundary for River Rch & Prof#=Deadman 75,Reach-1,4
Up Type=0
Dn Type=3
Dn Slope=0.009
Boundary for River Rch & Prof#=Deadman 75,Reach-1,5
Up Type=0
Dn Type=3
Dn Slope=0.009
Boundary for River Rch & Prof#=Deadman 75,Reach-1,6
Up Type=0
Dn Type=3
Dn Slope=0.009
Boundary for River Rch & Prof#=Deadman 75,Reach-1,7
Up Type=0
Dn Type=3
Dn Slope=0.009

--- Deadman 75.g01 (geometry) ---

Geom Title=Existing Conditions

River Reach=Deadman 75,Reach-1
Reach XY= 30
      1598955.00      6942588.00      1599070.21      6942588.51
      1599173.01      6942571.08      1599291.16      6942503.84
      1599500.40      6942495.02      1599665.74      6942463.05
      1599817.86      6942479.58      1599930.29      6942475.18
      1599982.62      6942488.41      1600189.78      6942488.52
      1600237.39      6942519.83      1600287.44      6942532.49
      1600380.03      6942528.09      1600420.82      6942551.23
      1600536.09      6942568.77      1600560.94      6942585.73
      1600699.06      6942590.27      1600763.63      6942618.47
      1601154.14      6942686.91      1601207.86      6942690.12
      1601288.33      6942655.95      1601318.09      6942663.67
      1601324.70      6942732.01      1601369.90      6942816.89
      1601540.75      6942889.64      1601576.03      6942888.54
      1601652.08      6942799.25      1601798.69      6942884.13
      1601848.95      6942886.43      1602005.00      6942738.00

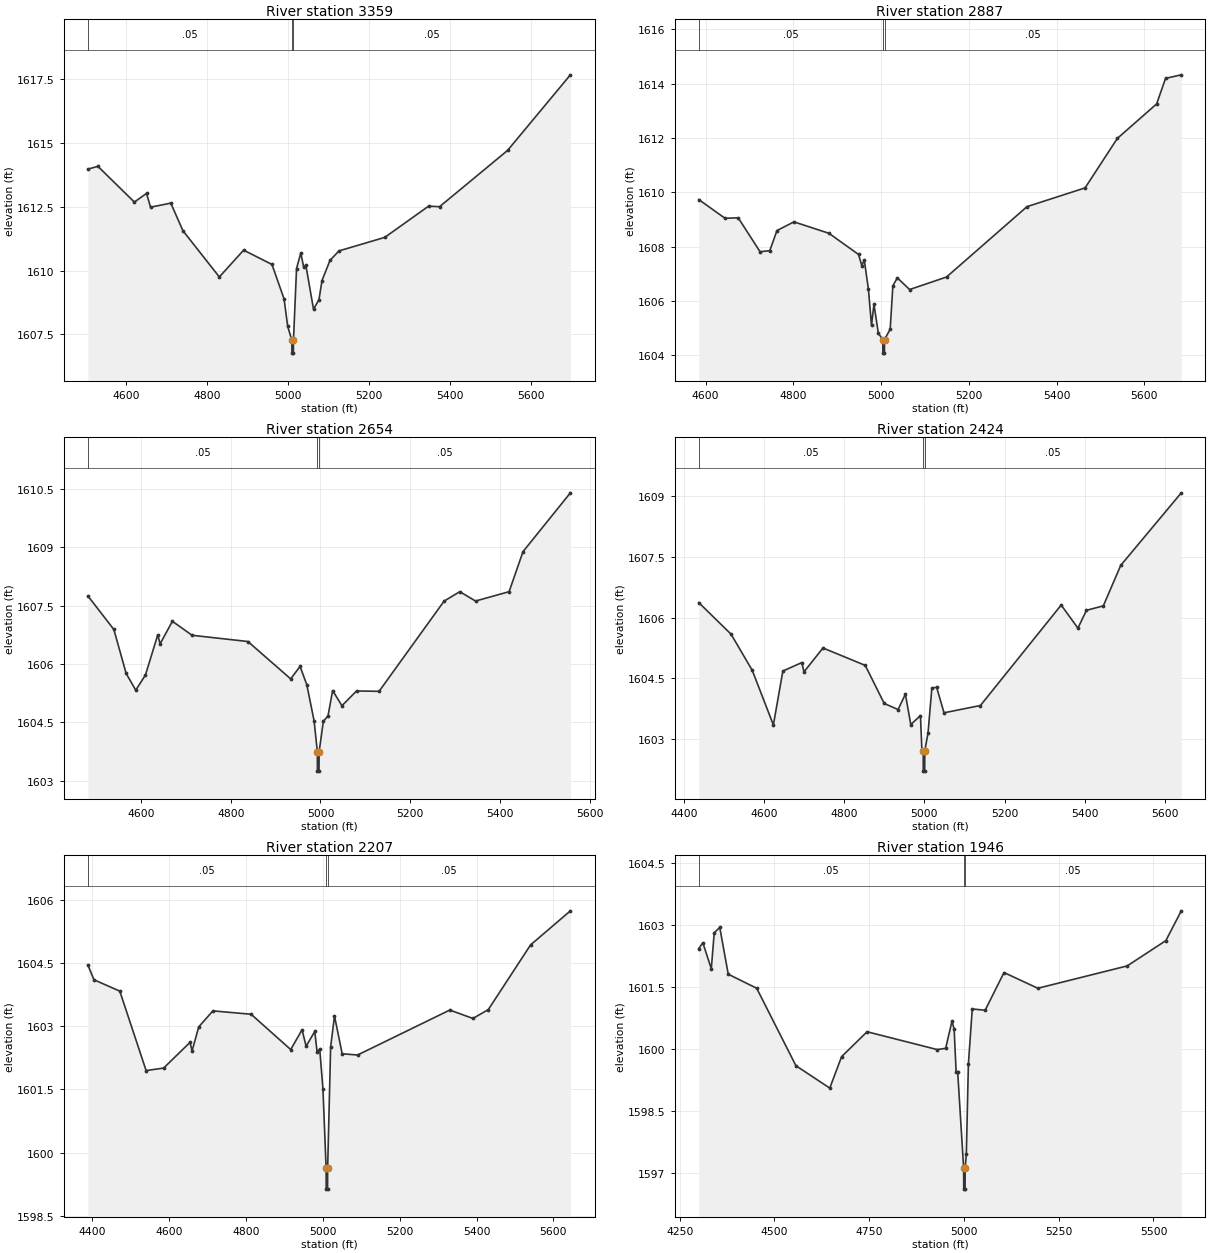
Type RM Length L Ch R = 1,3359,472,472,472
BEGIN DESCRIPTION:
Deadman 75 6.0
END DESCRIPTION:
XS GIS Cut Line= 3
      1598990.00      6943082.74      1598981.20      6942585.32
      1598774.68      6941921.81
#Sta/Elev= 30
  4505.3 1613.97  4530.0 1614.08  4620.1 1612.68  4650.1 1613.02  4660.1 1612.48
  4710.1 1612.64  4740.1 1611.56  4830.1 1609.75  4890.1 1610.80  4960.1 1610.24
  4990.1 1608.89  4999.0 1607.82  5009.3 1607.27  5009.5 1606.77  5013.0 1606.77
  5013.3 1607.27  5020.9 1610.08  5031.4 1610.69  5038.6 1610.13  5043.8 1610.22
  5062.8 1608.49  5076.3 1608.86  5083.8 1609.61  5103.6 1610.40  5125.7 1610.77
  5239.0 1611.30  5347.1 1612.52  5374.4 1612.50  5542.3 1614.70  5697.7 1617.66
#Mann=3,-1,0
  4505.3    0.05       0  5009.3    0.05       0  5013.3    0.05       0
Bank Sta=5009.3,5013.3
Exp/Cntr=0.3,0.1

Type RM Length L Ch R = 1,2887,233,233,233
BEGIN DESCRIPTION:
Deadman 75 5.0
END DESCRIPTION:
XS GIS Cut Line= 3
      1599237.77      6942871.13      1599439.02      6942484.07
      1599311.41      6941832.81
#Sta/Elev= 30
  4584.3 1609.73  4644.2 1609.04  4674.1 1609.06  4724.0 1607.81  4746.1 1607.85
  4762.5 1608.59  4801.1 1608.91  4880.9 1608.49  4948.5 1607.71  4955.9 1607.30
  4961.5 1607.51  4971.0 1606.43  4978.0 1605.10  4983.6 1605.88  4993.6 1604.81
  5003.7 1604.58  5004.0 1604.08  5007.5 1604.08  5007.7 1604.58  5020.6 1604.96
  5026.7 1606.56  5036.9 1606.85  5064.9 1606.42  5149.0 1606.88  5332.5 1609.47
  5464.9 1610.16  5538.4 1611.98  5628.0 1613.25  5648.3 1614.19  5684.2 1614.32
#Mann=3,-1,0
  4584.3    0.05       0  5003.7    0.05       0  5007.7    0.05       0
Bank Sta=5003.7,5007.7
Exp/Cntr=0.3,0.1

Type RM Length L Ch R = 1,2654,230,230,230
BEGIN DESCRIPTION:
Mapping XS 8b33ada0
END DESCRIPTION:
XS GIS Cut Line= 3
      1599523.42      6942959.81      1599667.61      6942493.70
      1599516.21      6941925.94
#Sta/Elev= 30
  4481.7 1607.75  4539.5 1606.89  4566.9 1605.76  4588.3 1605.33  4610.0 1605.72
  4637.3 1606.75  4642.6 1606.52  4670.0 1607.10  4713.9 1606.74  4838.3 1606.58
  4933.7 1605.62  4954.6 1605.94  4969.6 1605.47  4985.9 1604.54  4993.1 1603.75
  4993.3 1603.25  4996.8 1603.25  4997.1 1603.75  5006.5 1604.53  5016.9 1604.67
  5027.2 1605.32  5047.9 1604.93  5080.5 1605.31  5130.7 1605.30  5275.8 1607.62
  5310.7 1607.86  5345.7 1607.62  5420.5 1607.86  5451.6 1608.89  5557.2 1610.40
#Mann=3,-1,0
  4481.7    0.05       0  4993.1    0.03       0  4997.1    0.05       0
Bank Sta=4993.1,4997.1
Exp/Cntr=0.3,0.1

Type RM Length L Ch R = 1,2424,217,217,217
BEGIN DESCRIPTION:
Deadman 75 4.0
END DESCRIPTION:
XS GIS Cut Line= 3
      1599677.48      6942994.57      1599892.44      6942488.48
      1599663.52      6941876.55
#Sta/Elev= 30
  4437.5 1606.37  4518.0 1605.59  4570.7 1604.70  4623.5 1603.35  4647.1 1604.68
  4694.4 1604.89  4699.8 1604.66  4747.2 1605.25  4852.6 1604.82  4899.9 1603.88
  4934.5 1603.73  4952.7 1604.11  4966.1 1603.36  4990.3 1603.58  4993.8 1602.73
  4997.1 1602.71  4997.3 1602.21  5000.8 1602.21  5001.1 1602.71  5009.2 1603.16
  5018.7 1604.26  5030.6 1604.28  5049.0 1603.65  5139.8 1603.83  5341.2 1606.31
  5382.9 1605.74  5404.3 1606.18  5446.3 1606.29  5489.7 1607.29  5640.7 1609.08
#Mann=3,-1,0
  4437.5    0.05       0  4997.1    0.03       0  5001.1    0.05       0
Bank Sta=4997.1,5001.1
Exp/Cntr=0.3,0.1

Type RM Length L Ch R = 1,2207,261,261,261
BEGIN DESCRIPTION:
Mapping XS 858cdf4d
END DESCRIPTION:
XS GIS Cut Line= 3
      1599846.77      6943042.29      1600102.87      6942496.41
      1600115.85      6941844.40
#Sta/Elev= 30
  4389.1 1604.46  4404.9 1604.11  4472.0 1603.84  4540.5 1601.95  4586.1 1602.01
  4654.6 1602.62  4660.1 1602.42  4677.4 1602.99  4714.2 1603.37  4813.6 1603.29
  4916.6 1602.45  4946.1 1602.92  4956.7 1602.53  4979.3 1602.88  4985.1 1602.40
  4992.1 1602.46  5000.5 1601.51  5008.7 1599.63  5009.0 1599.13  5012.5 1599.13
  5012.7 1599.63  5020.5 1602.51  5030.5 1603.25  5050.5 1602.35  5090.5 1602.32
  5330.5 1603.39  5390.6 1603.19  5430.6 1603.40  5540.6 1604.94  5644.2 1605.75
#Mann=3,-1,0
  4389.1    0.05       0  5008.7    0.05       0  5012.7    0.05       0
Bank Sta=5008.7,5012.7
Exp/Cntr=0.3,0.1

Type RM Length L Ch R = 1,1946,172,172,172
BEGIN DESCRIPTION:
Deadman 75 3.0
END DESCRIPTION:
XS GIS Cut Line= 3
      1600050.94      6943157.56      1600354.66      6942545.70
      1600232.55      6941968.37
#Sta/Elev= 30
  4300.3 1602.43  4311.0 1602.57  4333.3 1601.94  4341.0 1602.81  4355.6 1602.94
  4378.0 1601.81  4453.1 1601.47  4556.6 1599.60  4645.9 1599.06  4677.2 1599.82
  4744.4 1600.42  4929.3 1599.99  4951.7 1600.02  4968.5 1600.68  4974.1 1600.48
  4979.3 1599.46  4983.4 1599.46  4999.2 1597.12  4999.4 1596.62  5002.9 1596.62
  5003.2 1597.12  5006.3 1597.47  5011.7 1599.64  5021.9 1600.97  5056.0 1600.94
  5105.7 1601.85  5194.9 1601.47  5430.8 1602.01  5532.7 1602.62  5573.5 1603.34
#Mann=3,-1,0
  4300.3    0.05       0  4999.2    0.05       0  5003.2    0.05       0
Bank Sta=4999.2,5003.2
Exp/Cntr=0.3,0.1

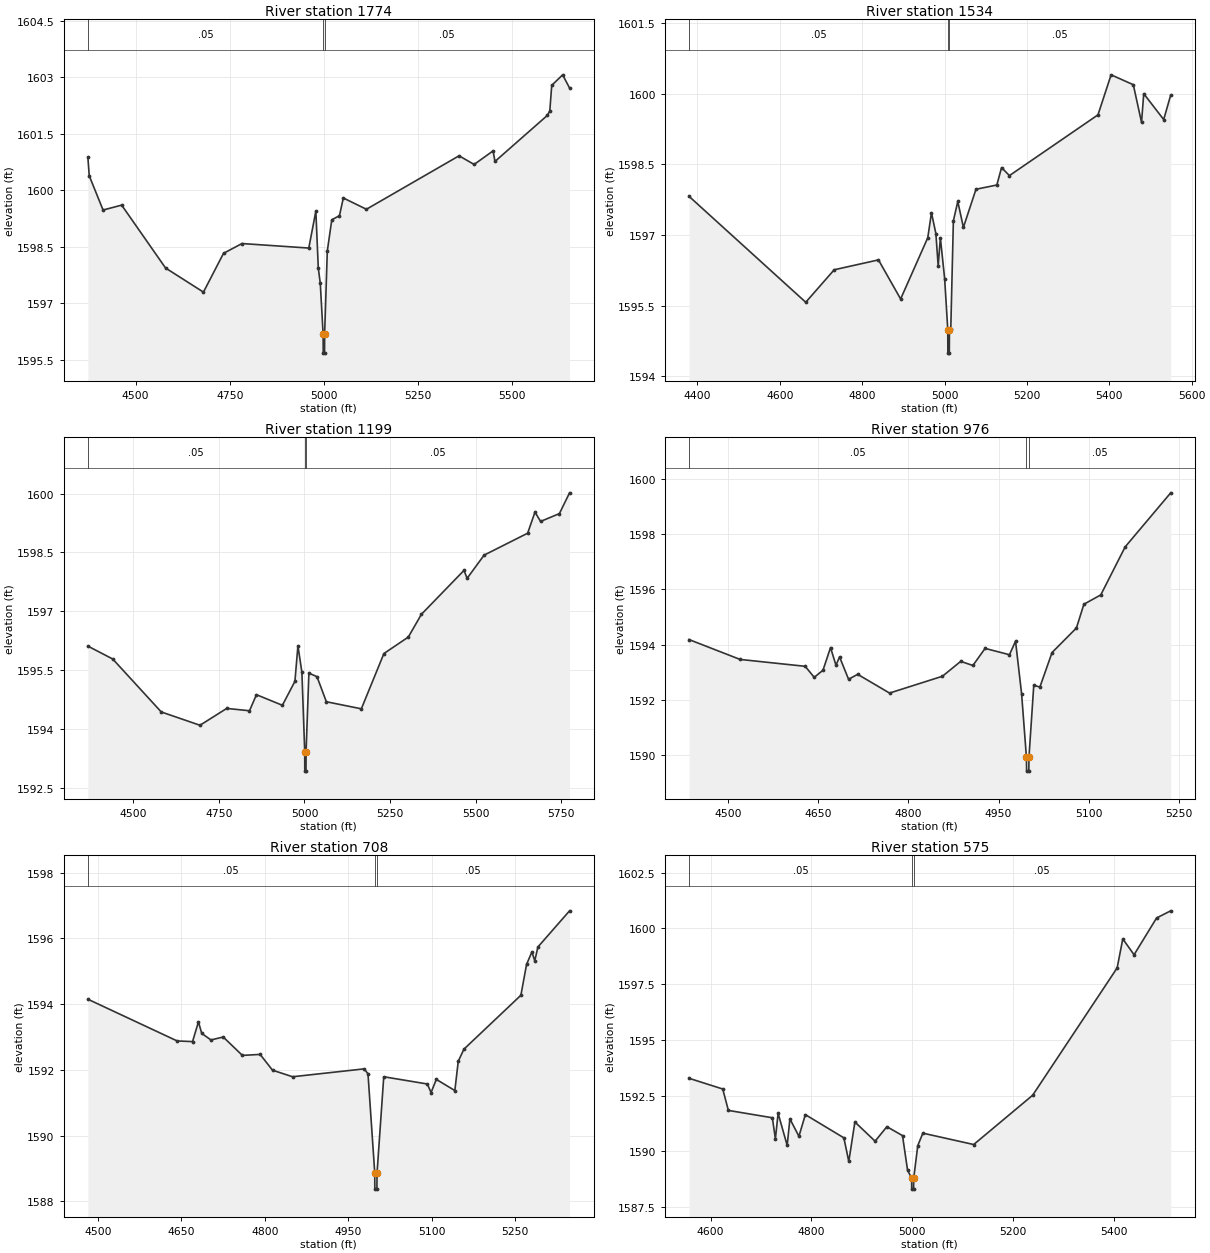
Type RM Length L Ch R = 1,1774,240,240,240
BEGIN DESCRIPTION:
Mapping XS f405339b
END DESCRIPTION:
XS GIS Cut Line= 3
      1600298.54      6943155.83      1600519.20      6942555.88
      1600389.72      6941930.07
#Sta/Elev= 30
  4373.5 1600.88  4377.1 1600.39  4413.8 1599.48  4463.2 1599.61  4579.7 1597.94
  4680.2 1597.30  4733.5 1598.33  4782.4 1598.59  4959.8 1598.47  4978.5 1599.45
  4985.0 1597.94  4990.3 1597.53  4997.8 1596.18  4998.1 1595.68  5001.6 1595.68
  5001.8 1596.18  5008.9 1598.39  5020.8 1599.22  5041.2 1599.33  5051.4 1599.80
  5112.7 1599.50  5358.6 1600.92  5398.6 1600.69  5448.8 1601.05  5453.9 1600.77
  5592.6 1601.99  5599.4 1602.11  5604.5 1602.79  5633.5 1603.07  5651.8 1602.72
#Mann=3,-1,0
  4373.5    0.05       0  4997.8    0.03       0  5001.8    0.05       0
Bank Sta=4997.8,5001.8
Exp/Cntr=0.3,0.1

Type RM Length L Ch R = 1,1534,335,335,335
BEGIN DESCRIPTION:
Deadman 75 2.0
END DESCRIPTION:
XS GIS Cut Line= 3
      1600565.06      6943185.57      1600768.46      6942673.37
      1600557.45      6942091.99
#Sta/Elev= 30
  4379.5 1597.82  4662.9 1595.57  4732.0 1596.26  4839.5 1596.47  4893.3 1595.64
  4959.2 1596.94  4968.2 1597.47  4978.9 1597.03  4984.5 1596.34  4989.8 1596.94
  5000.2 1596.07  5007.8 1594.99  5008.0 1594.49  5011.5 1594.49  5011.8 1594.99
  5015.1 1595.01  5021.4 1597.30  5032.1 1597.71  5045.7 1597.16  5076.3 1597.97
  5126.9 1598.06  5138.4 1598.43  5157.5 1598.26  5372.5 1599.55  5404.4 1600.40
  5458.3 1600.19  5478.3 1599.39  5483.6 1600.00  5532.1 1599.45  5549.1 1599.97
#Mann=3,-1,0
  4379.5    0.05       0  5007.8    0.03       0  5011.8    0.05       0
Bank Sta=5007.8,5011.8
Exp/Cntr=0.3,0.1

Type RM Length L Ch R = 1,1199,223,223,223
BEGIN DESCRIPTION:
Mapping XS 7c8fb3b9
END DESCRIPTION:
XS GIS Cut Line= 5
      1600749.54      6943194.21      1601034.63      6942859.00
      1601093.41      6942571.10      1600736.02      6942463.16
      1600630.12      6942183.66
#Sta/Elev= 30
  4367.7 1596.11  4440.3 1595.78  4581.9 1594.43  4695.0 1594.09  4773.0 1594.52
  4839.5 1594.46  4859.8 1594.87  4935.5 1594.60  4972.1 1595.21  4980.9 1596.12
  4992.5 1595.44  5000.7 1593.42  5000.9 1592.92  5004.4 1592.92  5004.7 1593.42
  5012.9 1595.42  5036.5 1595.33  5063.9 1594.69  5166.0 1594.51  5231.9 1595.92
  5303.1 1596.34  5341.3 1596.92  5465.5 1598.04  5474.9 1597.84  5524.3 1598.43
  5651.5 1598.99  5672.9 1599.53  5689.2 1599.29  5744.2 1599.49  5773.8 1600.02
#Mann=3,-1,0
  4367.7    0.05       0  5000.7    0.03       0  5004.7    0.05       0
Bank Sta=5000.7,5004.7
Exp/Cntr=0.3,0.1

Type RM Length L Ch R = 1,976,268,268,268
BEGIN DESCRIPTION:
Mapping XS a87f1195
END DESCRIPTION:
XS GIS Cut Line= 3
      1600989.42      6943079.96      1601246.44      6942909.34
      1601322.83      6942423.21
#Sta/Elev= 30
  4435.6 1594.18  4520.4 1593.46  4628.7 1593.21  4643.7 1592.81  4658.3 1593.07
  4670.8 1593.89  4679.8 1593.25  4685.8 1593.55  4700.8 1592.74  4715.9 1592.92
  4768.9 1592.24  4856.8 1592.85  4887.2 1593.39  4907.4 1593.24  4927.7 1593.86
  4968.2 1593.63  4978.3 1594.12  4988.4 1592.21  4996.4 1589.91  4996.7 1589.41
  5000.4 1589.41  5000.6 1589.91  5008.6 1592.52  5018.8 1592.46  5039.0 1593.71
  5079.5 1594.60  5091.9 1595.46  5120.0 1595.80  5160.5 1597.54  5236.2 1599.50
#Mann=3,-1,0
  4435.6    0.05       0  4996.4    0.05       0  5000.6    0.05       0
Bank Sta=4996.4,5000.6
Exp/Cntr=0.3,0.1

Type RM Length L Ch R = 1,708,133,133,133
BEGIN DESCRIPTION:
Mapping XS af9290c8
END DESCRIPTION:
XS GIS Cut Line= 4
      1600998.71      6943117.33      1601348.43      6942935.75
      1601506.74      6942766.57      1601456.84      6942532.48
#Sta/Elev= 30
  4482.3 1594.15  4642.6 1592.88  4670.3 1592.86  4680.9 1593.46  4686.8 1593.11
  4703.3 1592.91  4725.4 1593.00  4759.8 1592.44  4791.7 1592.47  4813.9 1591.99
  4850.0 1591.79  4978.5 1592.03  4985.4 1591.88  4997.5 1588.87  4997.7 1588.37
  5001.4 1588.37  5001.7 1588.87  5013.7 1591.79  5091.9 1591.57  5098.7 1591.31
  5108.1 1591.71  5141.4 1591.37  5147.5 1592.26  5157.7 1592.63  5260.0 1594.27
  5270.2 1595.21  5279.8 1595.59  5284.9 1595.32  5290.6 1595.74  5347.4 1596.84
#Mann=3,-1,0
  4482.3    0.05       0  4997.5    0.03       0  5001.7    0.05       0
Bank Sta=4997.5,5001.7
Exp/Cntr=0.3,0.1

Type RM Length L Ch R = 1,575,352,352,352
BEGIN DESCRIPTION:
Mapping XS 2c3d975b
END DESCRIPTION:
XS GIS Cut Line= 4
      1601183.48      6943091.96      1601549.87      6942931.49
      1601580.00      6942713.00      1601429.98      6942412.96
#Sta/Elev= 30
  4557.3 1593.28  4624.2 1592.80  4635.4 1591.84  4722.7 1591.51  4728.7 1590.56
  4734.1 1591.71  4752.1 1590.27  4757.5 1591.46  4775.4 1590.68  4788.2 1591.65
  4864.6 1590.61  4874.4 1589.55  4886.5 1591.32  4926.6 1590.46  4950.0 1591.11
  4981.0 1590.71  4991.1 1589.15  4999.1 1588.81  4999.3 1588.31  5003.0 1588.31
  5003.3 1588.81  5011.3 1590.26  5021.4 1590.82  5122.3 1590.31  5239.3 1592.52
  5407.0 1598.23  5418.2 1599.53  5440.6 1598.82  5485.3 1600.47  5513.3 1600.79
#Mann=3,-1,0
  4557.3    0.05       0  4999.1    0.03       0  5003.3    0.05       0
Bank Sta=4999.1,5003.3
Exp/Cntr=0.3,0.1

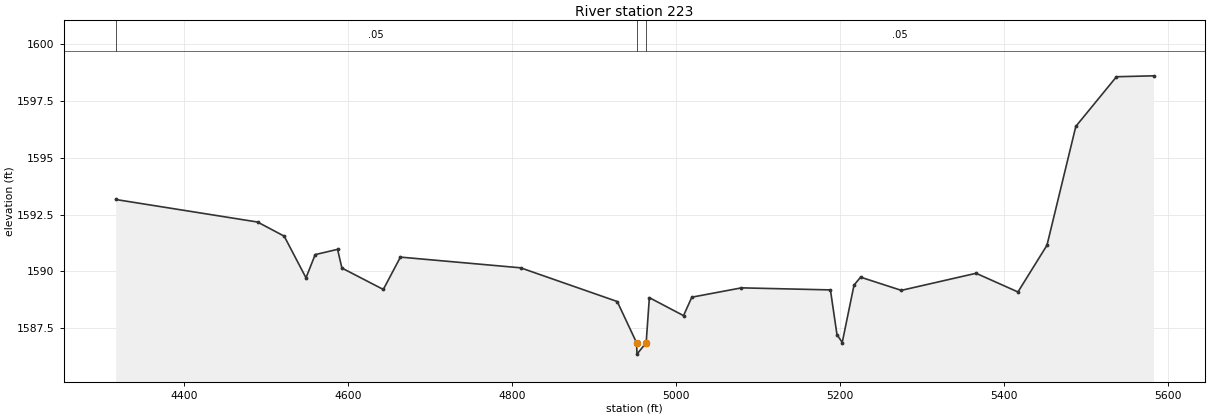
Type RM Length L Ch R = 1,223,0,0,0
BEGIN DESCRIPTION:
Deadman 75 1.0
END DESCRIPTION:
XS GIS Cut Line= 4
      1601193.28      6943093.96      1601840.84      6942892.54
      1601856.61      6942780.32      1601485.76      6942483.97
#Sta/Elev= 30
  4316.3 1593.16  4489.4 1592.17  4521.9 1591.55  4548.5 1589.72  4559.7 1590.74
  4587.0 1590.97  4592.3 1590.15  4642.8 1589.21  4663.7 1590.63  4810.3 1590.16
  4928.2 1588.68  4951.8 1586.87  4952.3 1586.37  4963.5 1586.87  4967.4 1588.85
  5009.1 1588.06  5019.2 1588.87  5079.8 1589.28  5188.3 1589.19  5196.3 1587.23
  5202.7 1586.88  5217.1 1589.40  5225.1 1589.75  5274.8 1589.17  5366.0 1589.92
  5417.1 1589.10  5452.5 1591.15  5487.7 1596.37  5537.3 1598.55  5582.5 1598.59
#Mann=3,-1,0
  4316.3    0.05       0  4951.8    0.03       0  4963.5    0.05       0
Bank Sta=4951.8,4963.5
Exp/Cntr=0.3,0.1

Chan Stop Cuts=-1