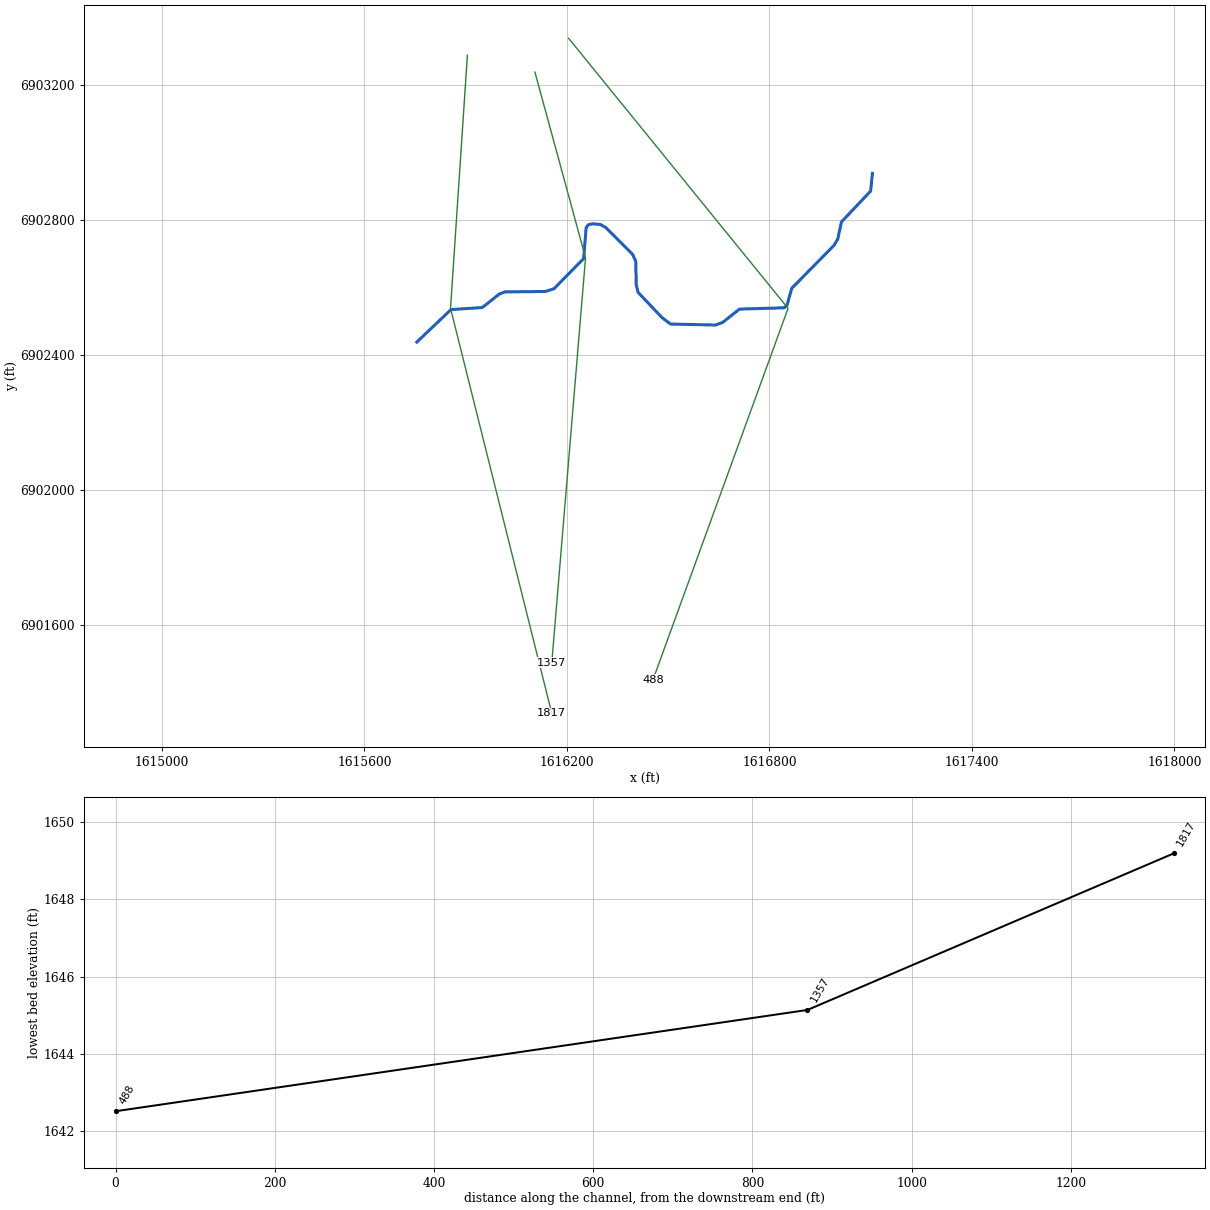
--- Deadman 76.prj (project) ---

Proj Title=Deadman 76 Base Level Engineering
Current Plan=p01
Default Exp/Contr=0.3,0.1
English Units
Geom File=g01
Flow File=f01
Plan File=p01
BEGIN DESCRIPTION:
Deadman 76
END DESCRIPTION:

--- Deadman 76.p01 (plan) ---

Plan Title=Multiple Run
Short Identifier=Multiple
Geom File=g01
Flow File=f01
Subcritical Flow
K Sum by GR= 0
Std Step Tol= 0.01
Critical Tol= 0.01
Num of Std Step Trials= 20
Max Error Tol= 0.3
Flow Tol Ratio= 0.001
Split Flow NTrial= 30
Split Flow Tol= 0.02
Split Flow Ratio= 0.02
Log Output Level= 0
Friction Slope Method= 1
Unsteady Friction Slope Method= 2
Unsteady Bridges Friction Slope Method= 1
Parabolic Critical Depth
Global Vel Dist=  1 , 1 , 1
Global Log Level= 0
CheckData=True
Encroach Param= -1, 0, 0, 0
BEGIN DESCRIPTION:
Multiple Run
END DESCRIPTION:

--- Deadman 76.f01 (steady flow) ---

Flow Title=Multiple
Number of Profiles=7
Profile Names=10-year,25-year,50-year,1pct_min,100-year,1pct_plu,500-year
River Rch & RM= Deadman 76,Reach-1,1817
     269     373     459     282     563    1123     854
Boundary for River Rch & Prof#=Deadman 76,Reach-1,1
Up Type=0
Dn Type=3
Dn Slope=0.005
Boundary for River Rch & Prof#=Deadman 76,Reach-1,2
Up Type=0
Dn Type=3
Dn Slope=0.005
Boundary for River Rch & Prof#=Deadman 76,Reach-1,3
Up Type=0
Dn Type=3
Dn Slope=0.005
Boundary for River Rch & Prof#=Deadman 76,Reach-1,4
Up Type=0
Dn Type=3
Dn Slope=0.005
Boundary for River Rch & Prof#=Deadman 76,Reach-1,5
Up Type=0
Dn Type=3
Dn Slope=0.005
Boundary for River Rch & Prof#=Deadman 76,Reach-1,6
Up Type=0
Dn Type=3
Dn Slope=0.005
Boundary for River Rch & Prof#=Deadman 76,Reach-1,7
Up Type=0
Dn Type=3
Dn Slope=0.005

--- Deadman 76.g01 (geometry) ---

Geom Title=Existing Conditions

River Reach=Deadman 76,Reach-1
Reach XY= 30
      1615755.00      6902438.00      1615856.48      6902534.44
      1615949.02      6902540.36      1615998.94      6902579.86
      1616015.51      6902586.77      1616135.01      6902587.98
      1616161.21      6902595.81      1616249.46      6902685.63
      1616256.74      6902776.81      1616263.17      6902785.55
      1616275.15      6902788.48      1616298.49      6902786.62
      1616314.40      6902777.96      1616394.49      6902697.81
      1616403.84      6902677.52      1616405.13      6902608.05
      1616410.52      6902585.56      1616481.42      6902510.83
      1616506.46      6902491.52      1616639.78      6902488.51
      1616661.05      6902496.14      1616710.95      6902535.72
      1616843.17      6902539.64      1616851.61      6902546.11
      1616865.91      6902597.37      1616991.37      6902724.79
      1617002.47      6902744.05      1617013.16      6902794.05
      1617099.67      6902885.49      1617105.00      6902938.00

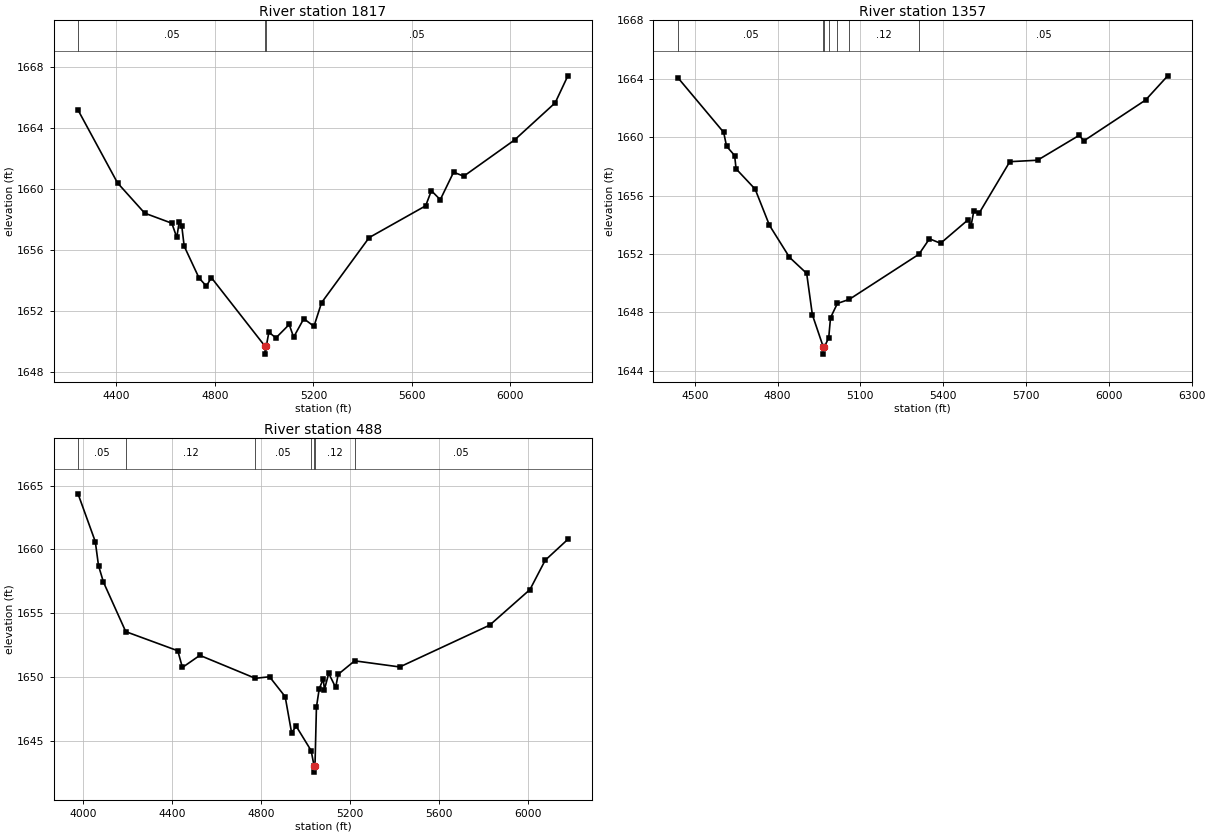
Type RM Length L Ch R = 1,1817,460,460,460
BEGIN DESCRIPTION:
Deadman 76 3.0
END DESCRIPTION:
XS GIS Cut Line= 3
      1615905.00      6903287.99      1615855.00      6902538.00
      1616155.00      6901337.98
#Sta/Elev= 30
  4244.3 1665.17  4404.6 1660.40  4514.9 1658.42  4625.1 1657.76  4645.2 1656.83
  4655.2 1657.86  4665.2 1657.61  4675.2 1656.26  4735.4 1654.18  4765.4 1653.64
  4785.5 1654.20  5004.2 1649.69  5004.4 1649.19  5008.4 1649.69  5019.1 1650.63
  5047.5 1650.25  5101.6 1651.13  5119.6 1650.30  5160.9 1651.51  5202.1 1651.01
  5233.0 1652.56  5426.3 1656.82  5655.6 1658.90  5678.8 1659.89  5714.9 1659.30
  5769.0 1661.10  5810.3 1660.84  6016.4 1663.21  6181.3 1665.64  6232.9 1667.41
#Mann=3,-1,0
  4244.3    0.05       0  5004.2    0.03       0  5008.4    0.05       0
Bank Sta=5004.2,5008.4
Exp/Cntr=0.3,0.1

Type RM Length L Ch R = 1,1357,869,869,869
BEGIN DESCRIPTION:
Deadman 76 2.0
END DESCRIPTION:
XS GIS Cut Line= 3
      1616105.01      6903237.97      1616255.00      6902688.00
      1616155.00      6901488.01
#Sta/Elev= 30
  4439.1 1664.07  4604.9 1660.33  4615.3 1659.38  4644.6 1658.74  4649.8 1657.83
  4718.9 1656.44  4770.8 1653.96  4843.3 1651.77  4905.5 1650.67  4926.2 1647.83
  4965.5 1645.64  4965.8 1645.14  4969.8 1645.64  4985.4 1646.26  4991.9 1647.63
  5016.7 1648.61  5059.8 1648.89  5312.1 1651.98  5350.3 1653.04  5390.5 1652.73
  5490.8 1654.35  5500.9 1653.94  5510.9 1654.93  5531.0 1654.82  5641.3 1658.32
  5741.7 1658.42  5892.2 1660.12  5909.8 1659.75  6133.0 1662.54  6213.3 1664.20
#Mann=7,-1,0
  4439.1    0.05       0  4965.5    0.07       0  4969.8    0.05       0
  4985.4    0.12       0  5016.7    0.05       0  5059.8    0.12       0
  5312.1    0.05       0
Bank Sta=4965.5,4969.8
Exp/Cntr=0.3,0.1

Type RM Length L Ch R = 1,488,0,0,0
BEGIN DESCRIPTION:
Deadman 76 1.0
END DESCRIPTION:
XS GIS Cut Line= 3
      1616204.98      6903338.02      1616855.00      6902538.00
      1616454.99      6901437.97
#Sta/Elev= 30
  3977.7 1664.35  4055.3 1660.60  4069.7 1658.72  4092.0 1657.42  4192.2 1653.54
  4426.0 1652.04  4446.8 1650.73  4525.1 1651.68  4774.4 1649.88  4838.3 1650.00
  4908.6 1648.44  4937.4 1645.61  4958.2 1646.12  5025.5 1644.20  5038.2 1643.02
  5038.5 1642.52  5042.6 1643.02  5049.1 1647.62  5061.7 1649.06  5079.7 1649.83
  5085.0 1649.00  5104.3 1650.27  5135.5 1649.16  5146.8 1650.19  5220.8 1651.25
  5423.5 1650.77  5827.8 1654.05  6008.7 1656.84  6077.2 1659.14  6179.0 1660.78
#Mann=7,-1,0
  3977.7    0.05       0  4192.2    0.12       0  4774.4    0.05       0
  5025.5    0.12       0  5038.2    0.05       0  5042.6    0.12       0
  5220.8    0.05       0
Bank Sta=5038.2,5042.6
Exp/Cntr=0.3,0.1

Chan Stop Cuts=-1