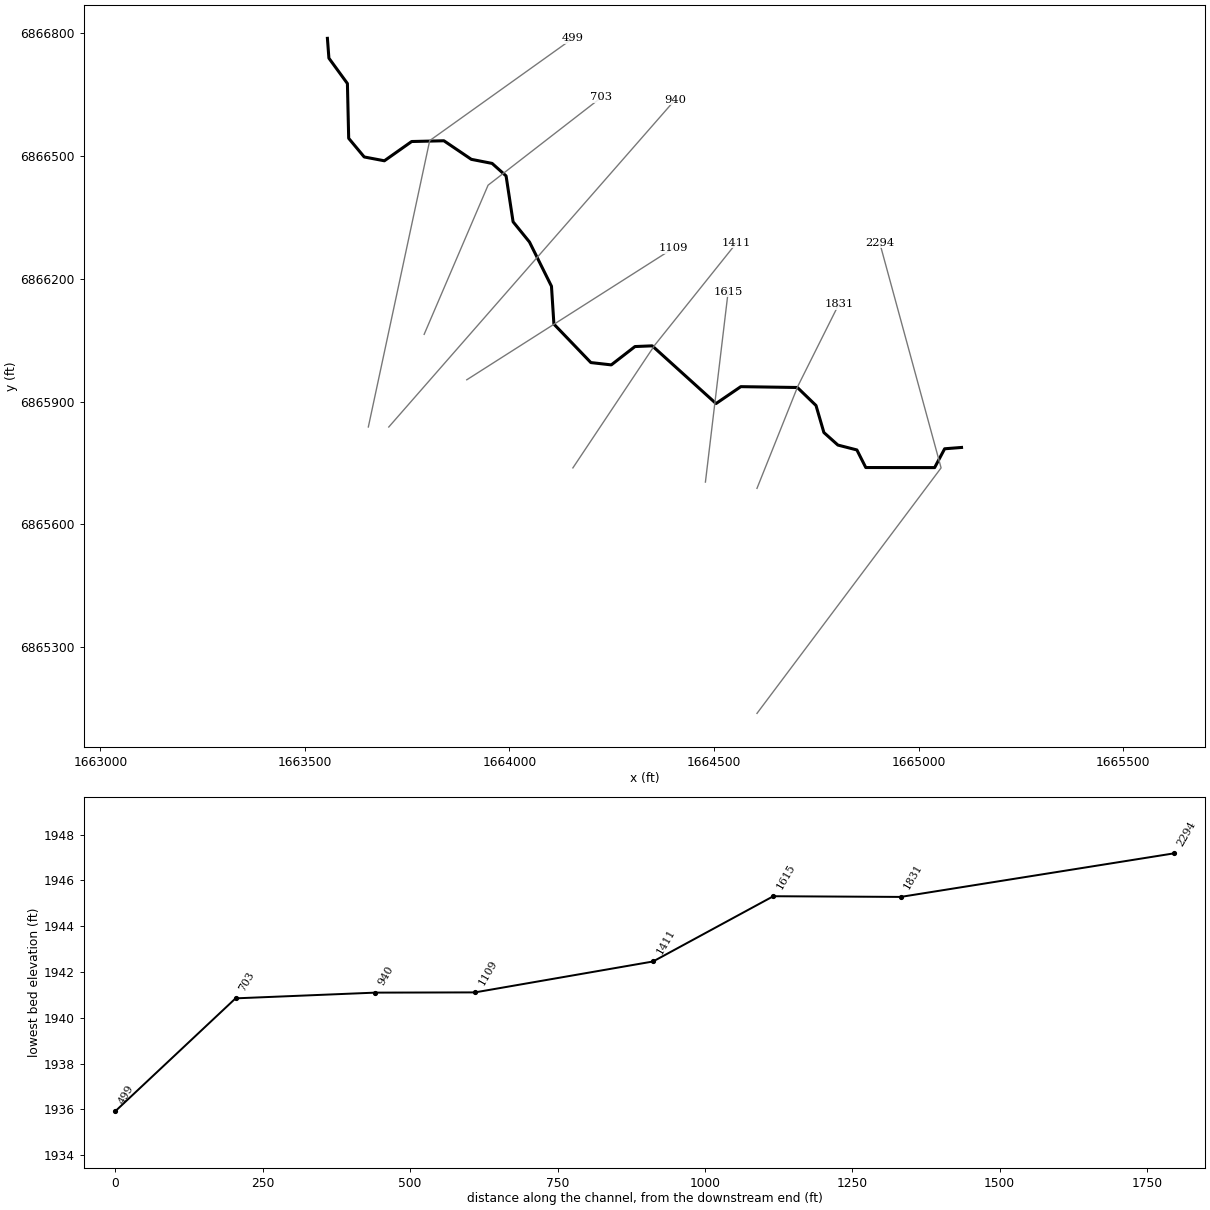
--- Deadman 77.prj (project) ---

Proj Title=Deadman 77 Base Level Engineering
Current Plan=p01
Default Exp/Contr=0.3,0.1
English Units
Geom File=g01
Flow File=f01
Plan File=p01
BEGIN DESCRIPTION:
Deadman 77
END DESCRIPTION:

--- Deadman 77.p01 (plan) ---

Plan Title=Multiple Run
Short Identifier=Multiple
Geom File=g01
Flow File=f01
Subcritical Flow
K Sum by GR= 0
Std Step Tol= 0.01
Critical Tol= 0.01
Num of Std Step Trials= 20
Max Error Tol= 0.3
Flow Tol Ratio= 0.001
Split Flow NTrial= 30
Split Flow Tol= 0.02
Split Flow Ratio= 0.02
Log Output Level= 0
Friction Slope Method= 1
Unsteady Friction Slope Method= 2
Unsteady Bridges Friction Slope Method= 1
Parabolic Critical Depth
Global Vel Dist=  1 , 1 , 1
Global Log Level= 0
CheckData=True
Encroach Param= -1, 0, 0, 0
BEGIN DESCRIPTION:
Multiple Run
END DESCRIPTION:

--- Deadman 77.f01 (steady flow) ---

Flow Title=Multiple
Number of Profiles=7
Profile Names=10-year,25-year,50-year,1pct_min,100-year,1pct_plu,500-year
River Rch & RM= Deadman 77,Reach-1,2294
     237     326     399     244     486     970     730
Boundary for River Rch & Prof#=Deadman 77,Reach-1,1
Up Type=0
Dn Type=3
Dn Slope=0.005
Boundary for River Rch & Prof#=Deadman 77,Reach-1,2
Up Type=0
Dn Type=3
Dn Slope=0.005
Boundary for River Rch & Prof#=Deadman 77,Reach-1,3
Up Type=0
Dn Type=3
Dn Slope=0.005
Boundary for River Rch & Prof#=Deadman 77,Reach-1,4
Up Type=0
Dn Type=3
Dn Slope=0.005
Boundary for River Rch & Prof#=Deadman 77,Reach-1,5
Up Type=0
Dn Type=3
Dn Slope=0.005
Boundary for River Rch & Prof#=Deadman 77,Reach-1,6
Up Type=0
Dn Type=3
Dn Slope=0.005
Boundary for River Rch & Prof#=Deadman 77,Reach-1,7
Up Type=0
Dn Type=3
Dn Slope=0.005

--- Deadman 77.g01 (geometry) ---

Geom Title=Existing Conditions

River Reach=Deadman 77,Reach-1
Reach XY= 30
      1665105.00      6865788.00      1665063.69      6865784.76
      1665039.24      6865738.76      1664870.94      6865738.91
      1664849.17      6865781.93      1664802.77      6865793.83
      1664768.55      6865824.47      1664749.26      6865890.55
      1664703.75      6865934.56      1664565.44      6865936.62
      1664504.90      6865895.32      1664348.96      6866036.38
      1664306.74      6866034.63      1664248.87      6865989.81
      1664198.93      6865995.48      1664108.61      6866089.48
      1664102.67      6866182.03      1664048.89      6866290.18
      1664008.83      6866339.59      1663991.74      6866451.66
      1663957.58      6866482.29      1663906.78      6866492.24
      1663839.73      6866537.63      1663760.96      6866535.81
      1663694.24      6866488.70      1663644.94      6866498.03
      1663606.99      6866543.63      1663603.87      6866677.53
      1663558.65      6866739.51      1663555.00      6866788.00

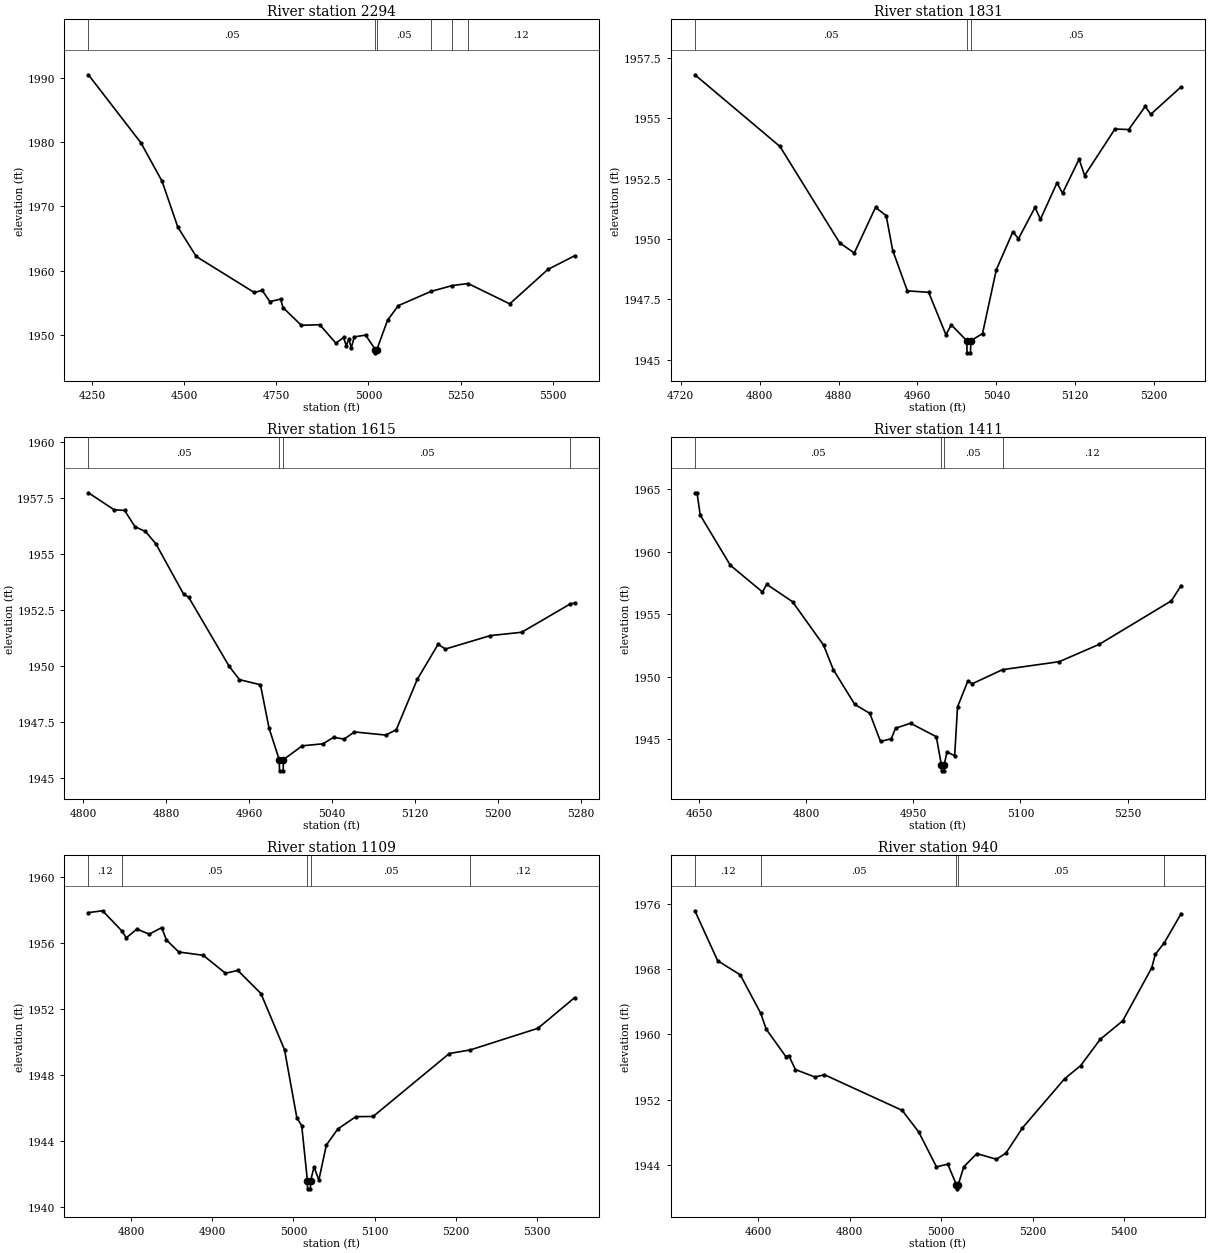
Type RM Length L Ch R = 1,2294,463,463,463
BEGIN DESCRIPTION:
Deadman 77 5.0
END DESCRIPTION:
XS GIS Cut Line= 3
      1664605.00      6865138.00      1665055.00      6865738.00
      1664905.00      6866288.01
#Sta/Elev= 30
  4239.7 1990.49  4382.4 1979.88  4439.7 1973.90  4482.4 1966.77  4532.4 1962.19
  4689.7 1956.59  4711.6 1956.90  4732.4 1955.16  4761.6 1955.55  4767.8 1954.24
  4817.8 1951.47  4867.8 1951.56  4911.6 1948.68  4932.4 1949.57  4939.7 1948.31
  4947.0 1949.34  4953.2 1947.94  4961.6 1949.67  4992.3 1949.94  5018.8 1947.68
  5019.0 1947.18  5022.8 1947.68  5051.9 1952.27  5081.3 1954.54  5169.5 1956.74
  5227.0 1957.65  5270.3 1957.98  5383.6 1954.81  5487.2 1960.17  5559.8 1962.30
#Mann=6,-1,0
  4239.7    0.05       0  5018.8    0.03       0  5022.8    0.05       0
  5169.5    0.12       0  5227.0    0.05       0  5270.3    0.12       0
Bank Sta=5018.8,5022.8
Exp/Cntr=0.3,0.1

Type RM Length L Ch R = 1,1831,216,216,216
BEGIN DESCRIPTION:
Deadman 77 4.0
END DESCRIPTION:
XS GIS Cut Line= 3
      1664604.99      6865687.97      1664705.00      6865938.00
      1664805.00      6866138.00
#Sta/Elev= 30
  4734.4 1956.81  4820.6 1953.84  4881.2 1949.84  4896.0 1949.42  4917.5 1951.31
  4928.3 1950.97  4935.0 1949.52  4949.8 1947.85  4971.4 1947.79  4988.9 1946.03
  4994.3 1946.44  5010.1 1945.78  5010.3 1945.28  5013.8 1945.28  5014.1 1945.78
  5026.0 1946.08  5040.0 1948.73  5056.8 1950.30  5062.4 1950.01  5079.2 1951.31
  5084.7 1950.82  5101.5 1952.33  5107.1 1951.90  5123.9 1953.31  5129.5 1952.63
  5160.2 1954.56  5174.2 1954.54  5191.0 1955.50  5196.5 1955.17  5227.3 1956.31
#Mann=3,-1,0
  4734.4    0.05       0  5010.1    0.05       0  5014.1    0.05       0
Bank Sta=5010.1,5014.1
Exp/Cntr=0.3,0.1

Type RM Length L Ch R = 1,1615,204,204,204
BEGIN DESCRIPTION:
Mapping XS 076412db
END DESCRIPTION:
XS GIS Cut Line= 2
      1664478.96      6865703.38      1664534.52      6866168.68
#Sta/Elev= 30
  4805.0 1957.75  4829.8 1956.99  4839.9 1956.96  4849.9 1956.23  4860.0 1956.02
  4870.1 1955.46  4896.7 1953.22  4901.7 1953.07  4940.6 1949.99  4950.6 1949.39
  4970.8 1949.16  4979.1 1947.22  4988.9 1945.81  4989.2 1945.31  4992.7 1945.31
  4992.9 1945.81  5011.1 1946.43  5031.2 1946.52  5041.3 1946.81  5051.4 1946.73
  5061.4 1947.05  5091.6 1946.91  5101.7 1947.15  5121.9 1949.40  5142.0 1950.97
  5149.1 1950.76  5192.3 1951.36  5222.6 1951.51  5269.1 1952.77  5273.6 1952.82
#Mann=4,-1,0
  4805.0    0.05       0  4988.9    0.05       0  4992.9    0.05       0
  5269.1    0.12       0
Bank Sta=4988.9,4992.9
Exp/Cntr=0.3,0.1

Type RM Length L Ch R = 1,1411,302,302,302
BEGIN DESCRIPTION:
Deadman 77 3.0
END DESCRIPTION:
XS GIS Cut Line= 3
      1664155.01      6865738.01      1664355.00      6866038.00
      1664555.00      6866288.00
#Sta/Elev= 30
  4644.2 1964.72  4647.2 1964.72  4651.7 1962.93  4693.8 1958.92  4738.8 1956.78
  4744.8 1957.39  4780.9 1956.00  4824.5 1952.51  4838.0 1950.56  4868.0 1947.78
  4889.1 1947.06  4904.1 1944.81  4919.1 1945.03  4925.1 1945.87  4946.1 1946.27
  4982.2 1945.19  4989.2 1942.96  4989.5 1942.46  4993.0 1942.46  4993.2 1942.96
  4997.2 1943.97  5007.9 1943.67  5011.9 1947.58  5026.3 1949.64  5032.8 1949.44
  5074.9 1950.56  5154.4 1951.20  5210.4 1952.59  5311.3 1956.07  5324.9 1957.29
#Mann=4,-1,0
  4644.2    0.05       0  4989.2    0.03       0  4993.2    0.05       0
  5074.9    0.12       0
Bank Sta=4989.2,4993.2
Exp/Cntr=0.3,0.1

Type RM Length L Ch R = 1,1109,169,169,169
BEGIN DESCRIPTION:
Mapping XS 10d9ff4f
END DESCRIPTION:
XS GIS Cut Line= 2
      1663895.62      6865953.37      1664401.25      6866275.45
#Sta/Elev= 30
  4747.2 1957.87  4764.7 1957.98  4788.2 1956.77  4793.9 1956.34  4807.0 1956.87
  4822.2 1956.56  4837.5 1956.96  4843.4 1956.21  4858.6 1955.48  4888.7 1955.28
  4916.2 1954.19  4931.4 1954.36  4959.9 1952.96  4989.0 1949.55  5004.2 1945.42
  5010.2 1944.94  5017.2 1941.61  5017.4 1941.11  5020.9 1941.11  5021.2 1941.61
  5025.4 1942.44  5031.3 1941.64  5040.6 1943.77  5054.7 1944.74  5077.0 1945.49
  5098.2 1945.50  5192.2 1949.32  5218.2 1949.54  5301.4 1950.85  5346.7 1952.71
#Mann=5,-1,0
  4747.2    0.12       0  4788.2    0.05       0  5017.2    0.05       0
  5021.2    0.05       0  5218.2    0.12       0
Bank Sta=5017.2,5021.2
Exp/Cntr=0.3,0.1

Type RM Length L Ch R = 1,940,237,237,237
BEGIN DESCRIPTION:
Deadman 77 2.0
END DESCRIPTION:
XS GIS Cut Line= 3
      1663705.00      6865838.00      1664055.00      6866238.00
      1664404.99      6866637.99
#Sta/Elev= 30
  4461.7 1975.12  4511.5 1969.01  4560.9 1967.28  4605.5 1962.60  4617.8 1960.62
  4660.5 1957.29  4667.2 1957.39  4681.4 1955.70  4724.1 1954.78  4745.0 1955.06
  4914.9 1950.70  4951.0 1948.06  4989.9 1943.79  5014.6 1944.12  5033.4 1941.60
  5033.7 1941.10  5037.4 1941.60  5049.7 1943.81  5078.2 1945.41  5120.9 1944.72
  5141.7 1945.46  5177.8 1948.55  5269.9 1954.56  5305.0 1956.17  5347.7 1959.38
  5397.1 1961.66  5460.6 1968.15  5468.2 1969.78  5487.9 1971.20  5524.7 1974.76
#Mann=5,-1,0
  4461.7    0.12       0  4605.5    0.05       0  5033.4    0.03       0
  5037.4    0.05       0  5487.9    0.12       0
Bank Sta=5033.4,5037.4
Exp/Cntr=0.3,0.1

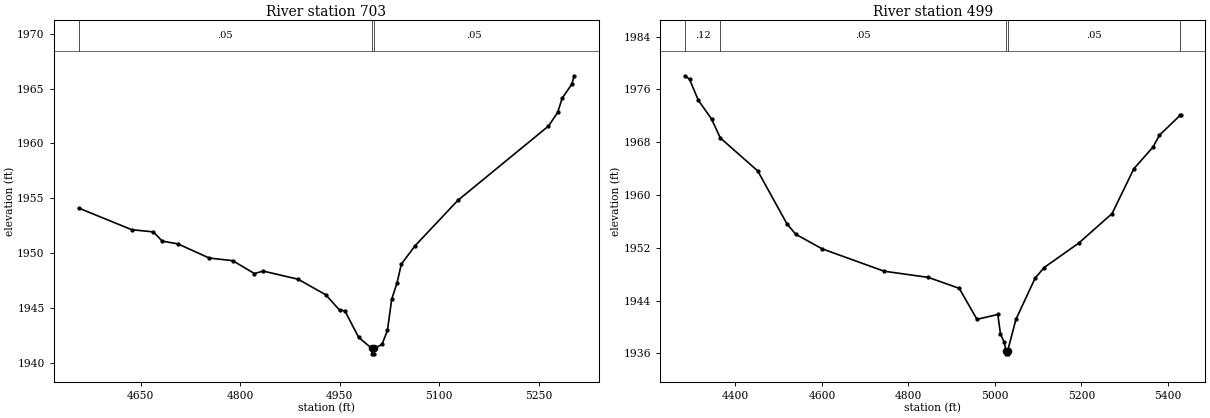
Type RM Length L Ch R = 1,703,204,204,204
BEGIN DESCRIPTION:
Mapping XS 75e8cd37
END DESCRIPTION:
XS GIS Cut Line= 3
      1663791.47      6866064.51      1663947.71      6866429.07
      1664224.65      6866643.70
#Sta/Elev= 30
  4556.4 1954.12  4636.4 1952.15  4669.0 1951.95  4682.4 1951.11  4706.0 1950.86
  4753.2 1949.57  4788.7 1949.33  4821.3 1948.16  4834.8 1948.38  4887.3 1947.64
  4929.1 1946.22  4949.7 1944.83  4957.7 1944.77  4978.5 1942.35  4998.2 1941.35
  4998.5 1940.85  5002.0 1940.85  5002.3 1941.35  5013.8 1941.71  5022.0 1943.01
  5028.3 1945.81  5036.4 1947.31  5042.8 1949.01  5063.6 1950.69  5127.9 1954.81
  5264.6 1961.58  5278.5 1962.82  5285.4 1964.13  5299.9 1965.40  5303.4 1966.16
#Mann=3,-1,0
  4556.4    0.05       0  4998.2    0.03       0  5002.3    0.05       0
Bank Sta=4998.2,5002.3
Exp/Cntr=0.3,0.1

Type RM Length L Ch R = 1,499,0,0,0
BEGIN DESCRIPTION:
Deadman 77 1.0
END DESCRIPTION:
XS GIS Cut Line= 3
      1663655.01      6865838.03      1663805.00      6866538.00
      1664155.02      6866788.01
#Sta/Elev= 30
  4283.5 1978.08  4293.7 1977.55  4314.2 1974.36  4344.8 1971.51  4365.0 1968.65
  4451.4 1963.66  4518.7 1955.67  4539.1 1954.06  4600.5 1951.84  4743.7 1948.45
  4846.0 1947.51  4917.5 1945.85  4958.5 1941.15  5006.7 1941.89  5012.9 1938.89
  5021.5 1937.70  5025.6 1936.42  5025.8 1935.92  5029.4 1935.92  5029.7 1936.42
  5048.5 1941.13  5092.8 1947.37  5113.7 1949.00  5193.5 1952.69  5271.0 1957.19
  5321.3 1963.99  5365.6 1967.27  5380.3 1969.06  5428.7 1972.11  5429.5 1972.11
#Mann=5,-1,0
  4283.5    0.12       0  4365.0    0.05       0  5025.6    0.03       0
  5029.7    0.05       0  5428.7    0.12       0
Bank Sta=5025.6,5029.7
Exp/Cntr=0.3,0.1

Chan Stop Cuts=-1