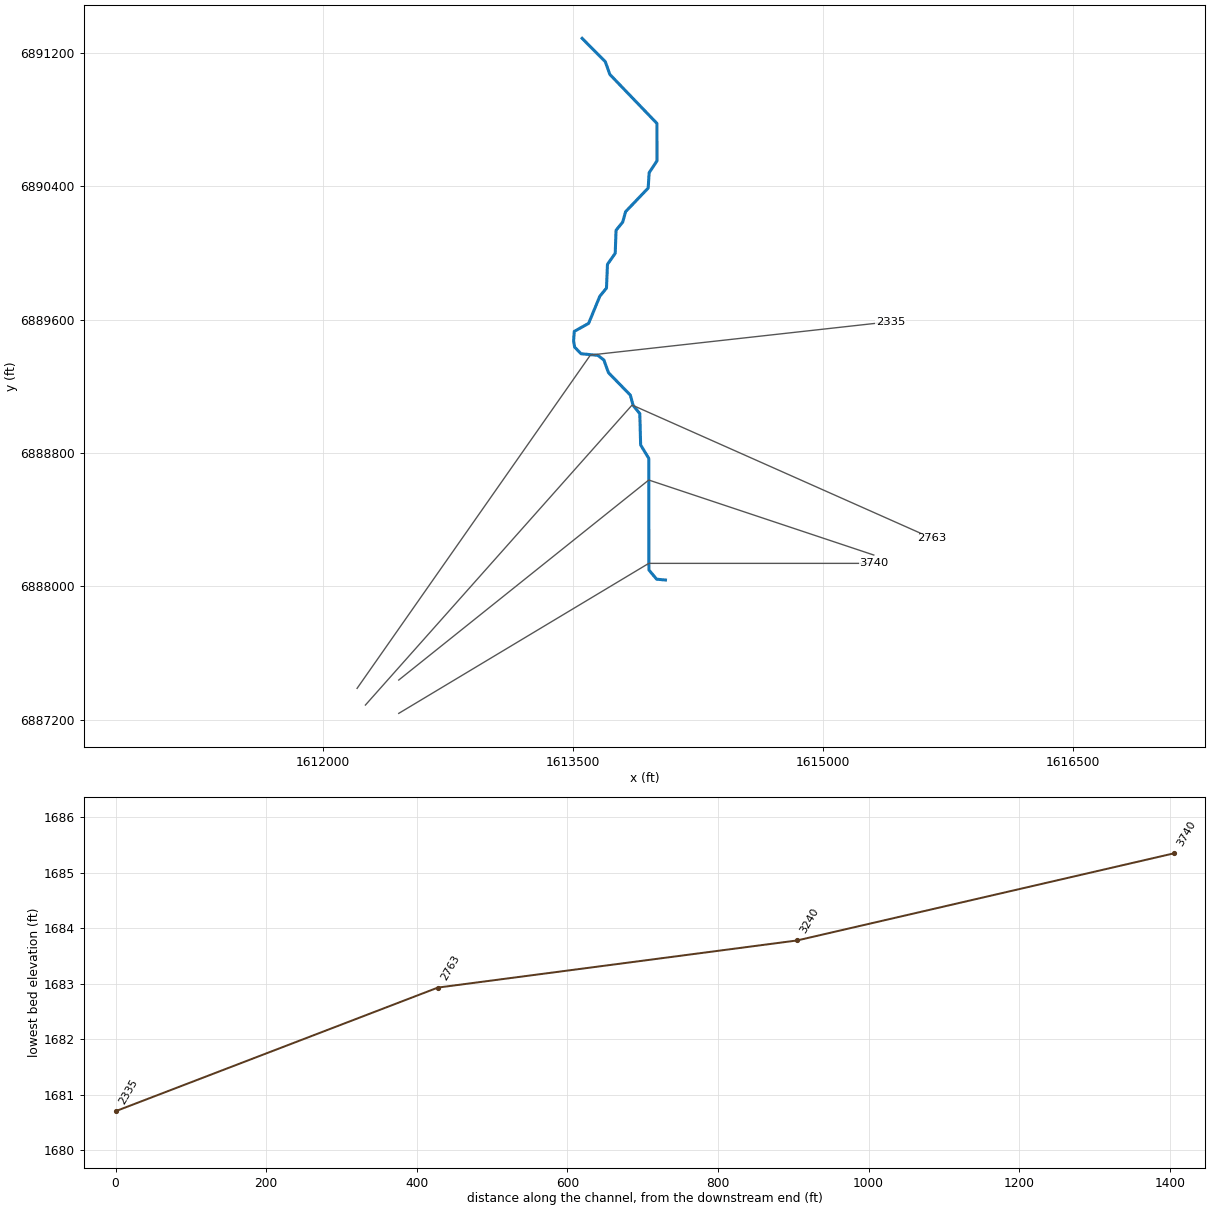
--- Deadman 78.prj (project) ---

Proj Title=Deadman 78 Base Level Engineering
Current Plan=p01
Default Exp/Contr=0.3,0.1
English Units
Geom File=g01
Flow File=f01
Plan File=p01
BEGIN DESCRIPTION:
Deadman 78
END DESCRIPTION:

--- Deadman 78.p01 (plan) ---

Plan Title=Multiple Run
Short Identifier=Multiple
Geom File=g01
Flow File=f01
Subcritical Flow
K Sum by GR= 0
Std Step Tol= 0.01
Critical Tol= 0.01
Num of Std Step Trials= 20
Max Error Tol= 0.3
Flow Tol Ratio= 0.001
Split Flow NTrial= 30
Split Flow Tol= 0.02
Split Flow Ratio= 0.02
Log Output Level= 0
Friction Slope Method= 1
Unsteady Friction Slope Method= 2
Unsteady Bridges Friction Slope Method= 1
Parabolic Critical Depth
Global Vel Dist=  1 , 1 , 1
Global Log Level= 0
CheckData=True
Encroach Param= -1, 0, 0, 0
BEGIN DESCRIPTION:
Multiple Run
END DESCRIPTION:

--- Deadman 78.f01 (steady flow) ---

Flow Title=Multiple
Number of Profiles=7
Profile Names=10-year,25-year,50-year,1pct_min,100-year,1pct_plu,500-year
River Rch & RM= Deadman 78,Reach-1,3740
     255     347     421     254     506    1010     742
Boundary for River Rch & Prof#=Deadman 78,Reach-1,1
Up Type=0
Dn Type=3
Dn Slope=0.005
Boundary for River Rch & Prof#=Deadman 78,Reach-1,2
Up Type=0
Dn Type=3
Dn Slope=0.005
Boundary for River Rch & Prof#=Deadman 78,Reach-1,3
Up Type=0
Dn Type=3
Dn Slope=0.005
Boundary for River Rch & Prof#=Deadman 78,Reach-1,4
Up Type=0
Dn Type=3
Dn Slope=0.005
Boundary for River Rch & Prof#=Deadman 78,Reach-1,5
Up Type=0
Dn Type=3
Dn Slope=0.005
Boundary for River Rch & Prof#=Deadman 78,Reach-1,6
Up Type=0
Dn Type=3
Dn Slope=0.005
Boundary for River Rch & Prof#=Deadman 78,Reach-1,7
Up Type=0
Dn Type=3
Dn Slope=0.005

--- Deadman 78.g01 (geometry) ---

Geom Title=Existing Conditions

River Reach=Deadman 78,Reach-1
Reach XY= 30
      1614055.00      6888038.00      1614002.05      6888043.13
      1613955.96      6888098.30      1613954.93      6888767.97
      1613906.22      6888848.51      1613901.25      6889036.45
      1613861.14      6889085.83      1613844.24      6889147.68
      1613713.17      6889281.97      1613685.41      6889358.57
      1613649.28      6889385.92      1613548.49      6889395.73
      1613510.25      6889435.35      1613504.08      6889473.11
      1613507.99      6889529.65      1613594.31      6889578.02
      1613661.12      6889740.18      1613701.24      6889789.56
      1613707.27      6889932.06      1613753.77      6889998.51
      1613758.76      6890136.44      1613798.86      6890185.83
      1613815.76      6890247.68      1613951.39      6890389.50
      1613957.36      6890482.02      1614004.48      6890553.22
      1614003.95      6890777.57      1613721.65      6891071.33
      1613694.23      6891147.68      1613555.00      6891288.00

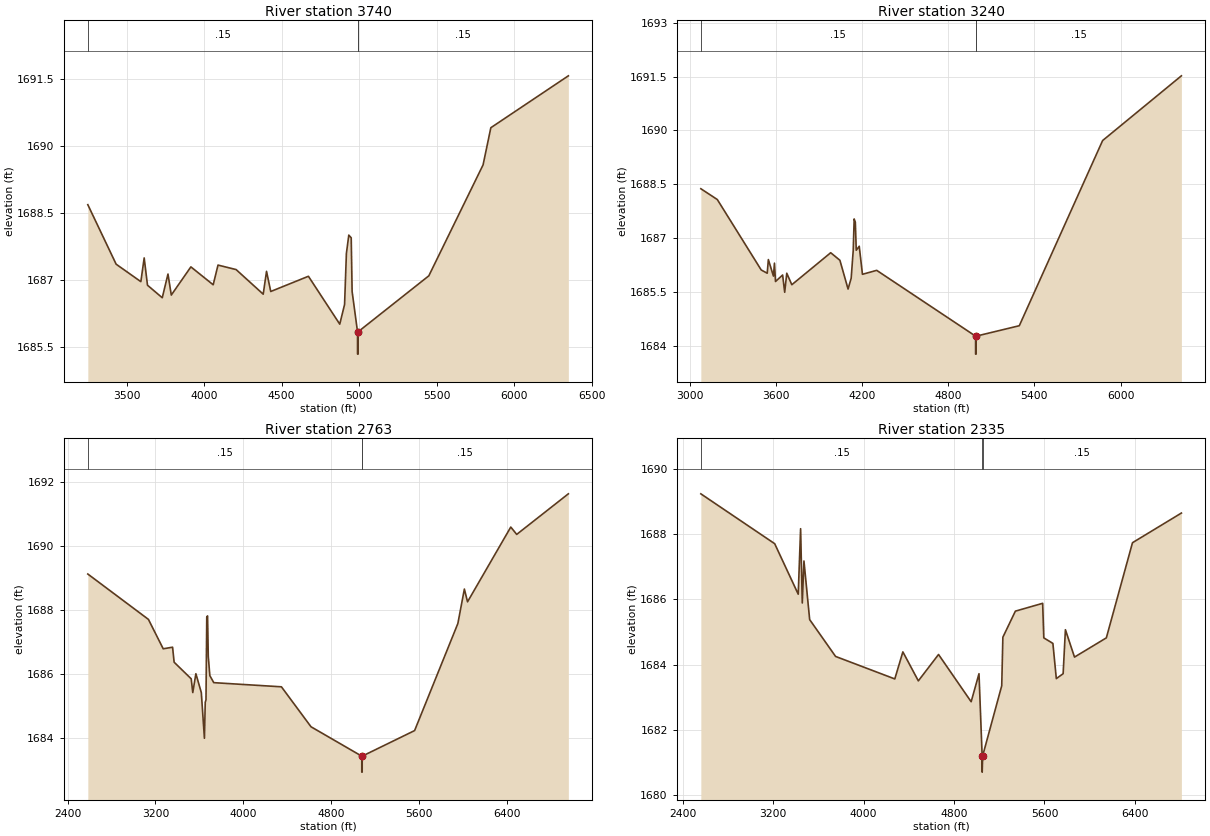
Type RM Length L Ch R = 1,3740,500,500,500
BEGIN DESCRIPTION:
Deadman 78 4.0
END DESCRIPTION:
XS GIS Cut Line= 3
      1612454.98      6887237.99      1613955.00      6888138.00
      1615304.99      6888138.00
#Sta/Elev= 30
  3249.8 1688.69  3432.5 1687.36  3591.9 1686.97  3613.3 1687.50  3634.7 1686.89
  3729.9 1686.61  3766.8 1687.14  3788.2 1686.67  3914.5 1687.30  4058.4 1686.90
  4089.5 1687.34  4206.1 1687.24  4381.0 1686.69  4402.4 1687.20  4429.6 1686.75
  4672.6 1687.09  4874.7 1686.02  4905.8 1686.46  4917.5 1687.60  4933.0 1688.01
  4948.6 1687.95  4954.4 1686.75  4989.3 1685.85  4989.6 1685.35  4993.1 1685.35
  4993.3 1685.85  5449.1 1687.10  5799.1 1689.58  5849.1 1690.41  6349.1 1691.57
#Mann=3,-1,0
  3249.8    0.15       0  4989.3    0.05       0  4993.3    0.15       0
Bank Sta=4989.3,4993.3
Exp/Cntr=0.3,0.1

Type RM Length L Ch R = 1,3240,477,477,477
BEGIN DESCRIPTION:
Deadman 78 3.0
END DESCRIPTION:
XS GIS Cut Line= 3
      1612454.98      6887437.98      1613955.00      6888638.00
      1615305.01      6888188.00
#Sta/Elev= 30
  3078.9 1688.38  3193.4 1688.08  3499.1 1686.12  3540.8 1686.03  3548.8 1686.41
  3584.0 1685.95  3591.2 1686.31  3598.4 1685.80  3648.0 1685.98  3662.4 1685.50
  3676.8 1686.03  3712.0 1685.71  3982.6 1686.60  4046.6 1686.39  4103.4 1685.59
  4125.0 1685.89  4139.4 1686.67  4145.8 1687.54  4153.9 1687.45  4160.3 1686.67
  4181.1 1686.78  4203.5 1686.00  4302.7 1686.11  4990.7 1684.28  4990.9 1683.78
  4994.4 1683.78  4994.7 1684.28  5295.0 1684.57  5874.8 1689.72  6422.9 1691.52
#Mann=3,-1,0
  3078.9    0.15       0  4990.7    0.05       0  4994.7    0.15       0
Bank Sta=4990.7,4994.7
Exp/Cntr=0.3,0.1

Type RM Length L Ch R = 1,2763,428,428,428
BEGIN DESCRIPTION:
Deadman 78 2.0
END DESCRIPTION:
XS GIS Cut Line= 3
      1612255.01      6887288.01      1613855.00      6889088.00
      1615655.03      6888287.99
#Sta/Elev= 30
  2584.2 1689.13  3136.5 1687.71  3271.1 1686.79  3356.4 1686.84  3370.6 1686.37
  3526.2 1685.85  3540.4 1685.42  3568.8 1686.01  3618.2 1685.42  3646.6 1683.99
  3654.1 1685.12  3660.8 1685.19  3667.9 1687.78  3675.0 1687.82  3681.7 1686.55
  3695.9 1685.95  3731.9 1685.73  4348.2 1685.60  4617.5 1684.35  5080.1 1683.43
  5080.3 1682.93  5083.8 1682.93  5084.1 1683.43  5561.5 1684.23  5955.5 1687.58
  6015.0 1688.66  6043.7 1688.26  6437.7 1690.60  6491.7 1690.37  6962.3 1691.64
#Mann=3,-1,0
  2584.2    0.15       0  5080.1    0.05       0  5084.1    0.15       0
Bank Sta=5080.1,5084.1
Exp/Cntr=0.3,0.1

Type RM Length L Ch R = 1,2335,0,0,0
BEGIN DESCRIPTION:
Deadman 78 1.0
END DESCRIPTION:
XS GIS Cut Line= 3
      1612205.02      6887388.03      1613605.00      6889388.00
      1615405.04      6889588.00
#Sta/Elev= 30
  2559.5 1689.24  3213.0 1687.71  3421.3 1686.16  3442.3 1688.17  3457.1 1685.89
  3471.9 1687.18  3522.5 1685.38  3751.8 1684.25  4275.8 1683.56  4347.3 1684.39
  4484.2 1683.50  4662.9 1684.31  4951.5 1682.86  5020.9 1683.72  5048.8 1681.20
  5049.1 1680.70  5053.4 1681.20  5222.1 1683.35  5232.2 1684.84  5342.9 1685.64
  5584.3 1685.88  5594.4 1684.82  5674.9 1684.65  5705.1 1683.57  5765.5 1683.72
  5785.6 1685.07  5866.1 1684.23  6147.8 1684.82  6379.2 1687.74  6811.9 1688.65
#Mann=3,-1,0
  2559.5    0.15       0  5048.8    0.05       0  5053.4    0.15       0
Bank Sta=5048.8,5053.4
Exp/Cntr=0.3,0.1

Chan Stop Cuts=-1