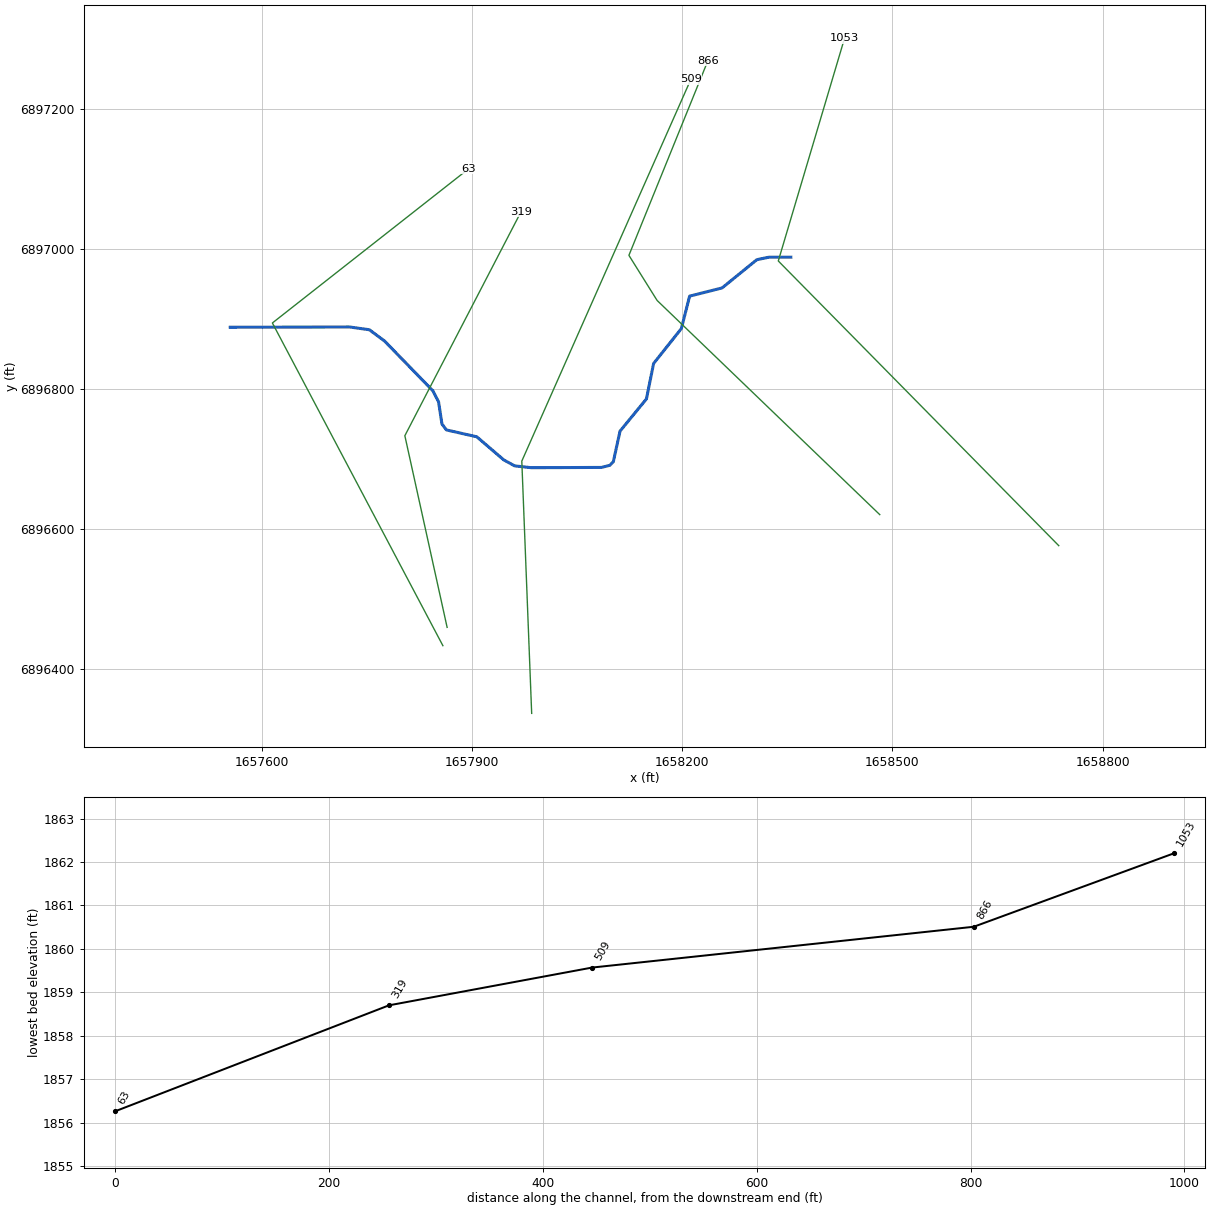
--- Deadman 79.prj (project) ---

Proj Title=Deadman 79 Base Level Engineering
Current Plan=p01
Default Exp/Contr=0.3,0.1
English Units
Geom File=g01
Flow File=f01
Plan File=p01
BEGIN DESCRIPTION:
Deadman 79
END DESCRIPTION:

--- Deadman 79.p01 (plan) ---

Plan Title=Multiple Run
Short Identifier=Multiple
Geom File=g01
Flow File=f01
Subcritical Flow
K Sum by GR= 0
Std Step Tol= 0.01
Critical Tol= 0.01
Num of Std Step Trials= 20
Max Error Tol= 0.3
Flow Tol Ratio= 0.001
Split Flow NTrial= 30
Split Flow Tol= 0.02
Split Flow Ratio= 0.02
Log Output Level= 0
Friction Slope Method= 1
Unsteady Friction Slope Method= 2
Unsteady Bridges Friction Slope Method= 1
Parabolic Critical Depth
Global Vel Dist=  1 , 1 , 1
Global Log Level= 0
CheckData=True
Encroach Param= -1, 0, 0, 0
BEGIN DESCRIPTION:
Multiple Run
END DESCRIPTION:

--- Deadman 79.f01 (steady flow) ---

Flow Title=Multiple
Number of Profiles=7
Profile Names=10-year,25-year,50-year,1pct_min,100-year,1pct_plu,500-year
River Rch & RM= Deadman 79,Reach-1,1053
     229     315     386     236     471     940     709
River Rch & RM= Deadman 79,Reach-1,866
     237     327     401     246     490     978     740
Boundary for River Rch & Prof#=Deadman 79,Reach-1,1
Up Type=0
Dn Type=3
Dn Slope=0.009
Boundary for River Rch & Prof#=Deadman 79,Reach-1,2
Up Type=0
Dn Type=3
Dn Slope=0.009
Boundary for River Rch & Prof#=Deadman 79,Reach-1,3
Up Type=0
Dn Type=3
Dn Slope=0.009
Boundary for River Rch & Prof#=Deadman 79,Reach-1,4
Up Type=0
Dn Type=3
Dn Slope=0.009
Boundary for River Rch & Prof#=Deadman 79,Reach-1,5
Up Type=0
Dn Type=3
Dn Slope=0.009
Boundary for River Rch & Prof#=Deadman 79,Reach-1,6
Up Type=0
Dn Type=3
Dn Slope=0.009
Boundary for River Rch & Prof#=Deadman 79,Reach-1,7
Up Type=0
Dn Type=3
Dn Slope=0.009

--- Deadman 79.g01 (geometry) ---

Geom Title=Existing Conditions

River Reach=Deadman 79,Reach-1
Reach XY= 24
      1658355.00      6896988.00      1658323.17      6896987.91
      1658306.45      6896984.42      1658256.87      6896944.13
      1658210.56      6896932.44      1658198.76      6896886.15
      1658159.15      6896836.30      1658148.94      6896785.77
      1658111.27      6896739.79      1658101.65      6896696.08
      1658096.72      6896691.05      1658084.81      6896688.02
      1657984.89      6896687.59      1657960.92      6896690.21
      1657945.28      6896698.77      1657906.84      6896731.72
      1657863.48      6896741.51      1657857.12      6896750.01
      1657852.31      6896781.57      1657844.12      6896797.44
      1657775.20      6896868.41      1657753.55      6896884.47
      1657725.19      6896888.45      1657555.00      6896888.00

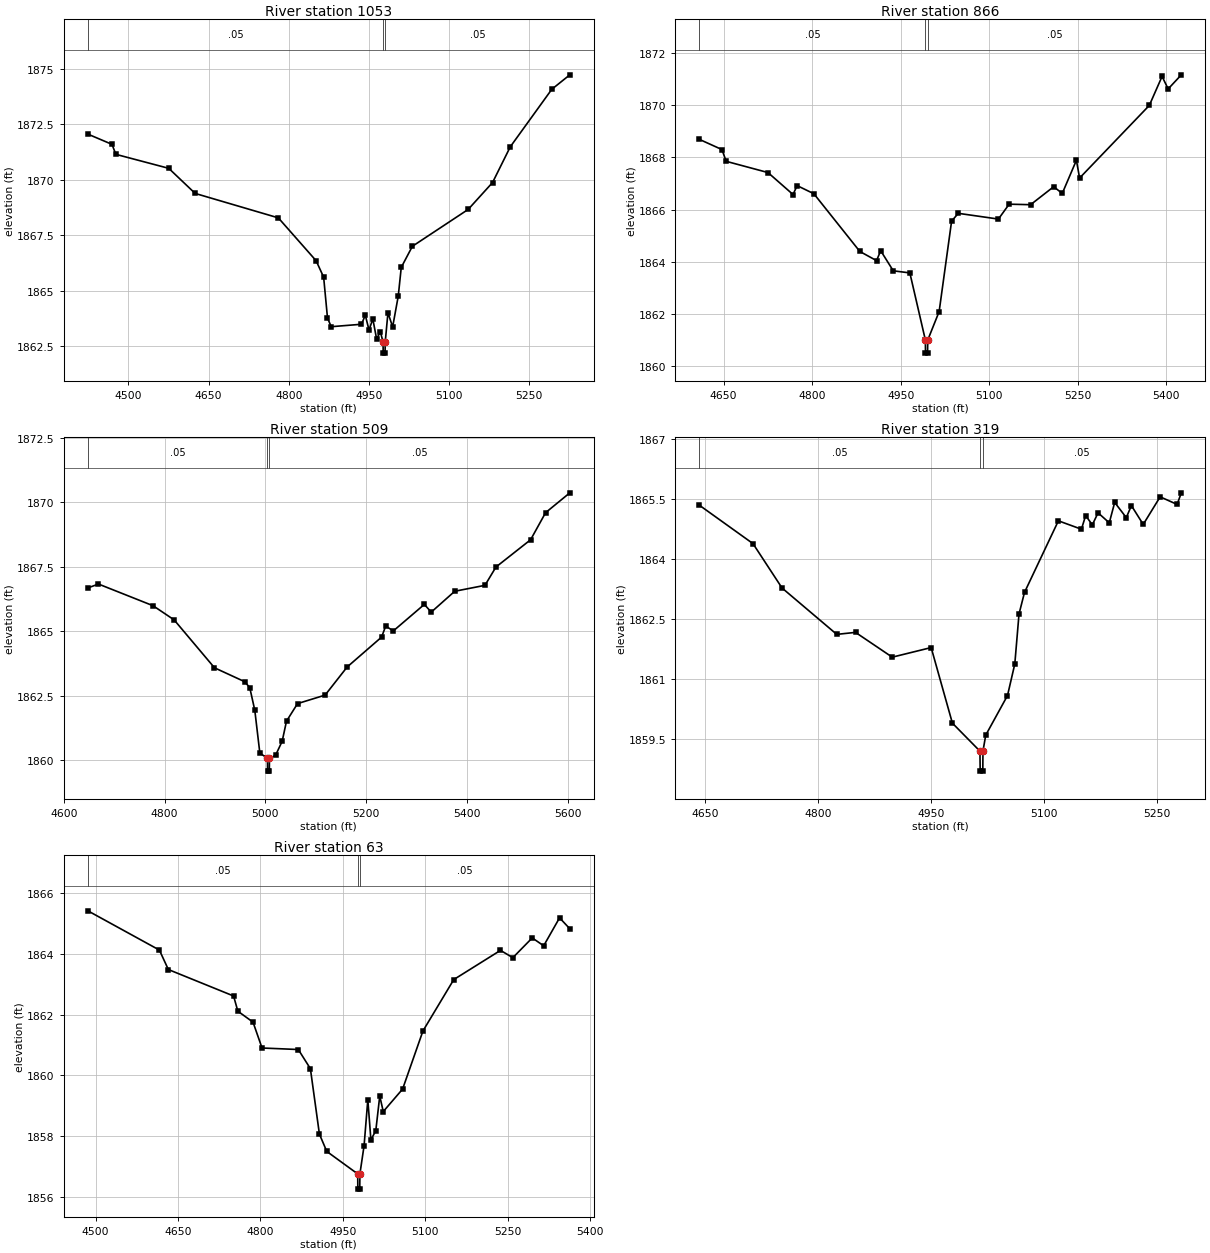
Type RM Length L Ch R = 1,1053,187,187,187
BEGIN DESCRIPTION:
Deadman 79 2.0
END DESCRIPTION:
XS GIS Cut Line= 3
      1658737.28      6896576.40      1658337.10      6896982.62
      1658431.61      6897300.33
#Sta/Elev= 30
  4424.2 1872.06  4469.3 1871.60  4476.5 1871.15  4575.5 1870.52  4624.9 1869.39
  4780.5 1868.29  4851.2 1866.36  4865.3 1865.62  4872.5 1863.78  4879.5 1863.39
  4936.1 1863.50  4943.2 1863.91  4950.2 1863.24  4957.3 1863.74  4964.3 1862.85
  4971.5 1863.15  4976.5 1862.70  4976.7 1862.20  4980.2 1862.20  4980.5 1862.70
  4985.6 1864.02  4994.4 1863.38  5004.9 1864.77  5010.5 1866.06  5031.3 1867.01
  5135.7 1868.67  5181.3 1869.88  5214.5 1871.49  5292.2 1874.08  5325.9 1874.73
#Mann=3,-1,0
  4424.2    0.05       0  4976.5    0.03       0  4980.5    0.05       0
Bank Sta=4976.5,4980.5
Exp/Cntr=0.3,0.1

Type RM Length L Ch R = 1,866,357,357,357
BEGIN DESCRIPTION:
Mapping XS 11f03e65
END DESCRIPTION:
XS GIS Cut Line= 4
      1658481.87      6896620.65      1658164.15      6896926.31
      1658123.93      6896990.66      1658236.56      6897268.22
#Sta/Elev= 30
  4609.1 1868.69  4647.3 1868.30  4654.5 1867.85  4725.3 1867.42  4767.7 1866.58
  4774.7 1866.92  4803.0 1866.61  4880.9 1864.40  4909.2 1864.05  4916.2 1864.43
  4937.5 1863.66  4965.6 1863.58  4991.9 1861.01  4992.1 1860.51  4995.6 1860.51
  4995.9 1861.01  5015.2 1862.10  5036.3 1865.56  5047.6 1865.86  5115.6 1865.64
  5133.8 1866.21  5170.1 1866.19  5209.3 1866.88  5223.7 1866.62  5247.7 1867.89
  5253.1 1867.21  5371.2 1869.99  5392.8 1871.10  5403.1 1870.62  5425.4 1871.16
#Mann=3,-1,0
  4609.1    0.05       0  4991.9    0.03       0  4995.9    0.05       0
Bank Sta=4991.9,4995.9
Exp/Cntr=0.3,0.1

Type RM Length L Ch R = 1,509,190,190,190
BEGIN DESCRIPTION:
Mapping XS 8f4617cb
END DESCRIPTION:
XS GIS Cut Line= 3
      1657985.17      6896337.03      1657971.09      6896697.05
      1658212.41      6897242.02
#Sta/Elev= 30
  4647.7 1866.68  4668.7 1866.83  4776.9 1865.99  4818.8 1865.44  4898.9 1863.58
  4958.9 1863.04  4968.9 1862.81  4978.9 1861.93  4988.9 1860.27  5004.0 1860.07
  5004.2 1859.57  5007.7 1859.57  5008.0 1860.07  5020.0 1860.18  5033.2 1860.73
  5041.8 1861.51  5063.7 1862.19  5118.4 1862.52  5162.1 1863.61  5230.4 1864.77
  5238.7 1865.20  5253.7 1865.01  5315.3 1866.04  5329.0 1865.74  5375.6 1866.55
  5435.6 1866.78  5457.4 1867.49  5526.2 1868.55  5555.9 1869.60  5604.0 1870.37
#Mann=3,-1,0
  4647.7    0.05       0  5004.0    0.03       0  5008.0    0.05       0
Bank Sta=5004,5008
Exp/Cntr=0.3,0.1

Type RM Length L Ch R = 1,319,256,256,256
BEGIN DESCRIPTION:
Mapping XS cb11a29e
END DESCRIPTION:
XS GIS Cut Line= 3
      1657864.51      6896459.76      1657804.18      6896733.25
      1657970.01      6897052.93
#Sta/Elev= 30
  4642.6 1865.35  4713.8 1864.39  4752.4 1863.28  4825.1 1862.12  4850.0 1862.17
  4898.8 1861.55  4950.5 1861.79  4978.7 1859.90  5015.3 1859.20  5015.6 1858.70
  5019.1 1858.70  5019.3 1859.20  5023.0 1859.60  5051.9 1860.59  5061.6 1861.38
  5067.2 1862.63  5074.5 1863.17  5119.5 1864.96  5150.1 1864.75  5155.7 1865.09
  5164.6 1864.86  5172.2 1865.16  5187.1 1864.91  5194.3 1865.42  5209.7 1865.04
  5216.5 1865.34  5232.2 1864.87  5254.7 1865.56  5277.2 1865.37  5282.8 1865.66
#Mann=3,-1,0
  4642.6    0.05       0  5015.3    0.03       0  5019.3    0.05       0
Bank Sta=5015.3,5019.3
Exp/Cntr=0.3,0.1

Type RM Length L Ch R = 1,63,0,0,0
BEGIN DESCRIPTION:
Deadman 79 1.0
END DESCRIPTION:
XS GIS Cut Line= 3
      1657858.47      6896433.62      1657615.15      6896894.13
      1657895.20      6897114.17
#Sta/Elev= 30
  4485.9 1865.41  4616.0 1864.12  4632.3 1863.48  4751.0 1862.61  4758.8 1862.11
  4786.4 1861.75  4802.8 1860.90  4868.8 1860.85  4890.8 1860.22  4907.2 1858.07
  4920.6 1857.50  4976.9 1856.76  4977.1 1856.26  4980.6 1856.26  4980.9 1856.76
  4988.5 1857.69  4995.3 1859.20  5000.9 1857.88  5009.8 1858.18  5017.0 1859.32
  5023.4 1858.81  5058.6 1859.55  5095.6 1861.46  5151.7 1863.15  5236.7 1864.11
  5259.2 1863.87  5294.5 1864.52  5315.3 1864.26  5344.2 1865.18  5362.9 1864.82
#Mann=3,-1,0
  4485.9    0.05       0  4976.9    0.03       0  4980.9    0.05       0
Bank Sta=4976.9,4980.9
Exp/Cntr=0.3,0.1

Chan Stop Cuts=-1