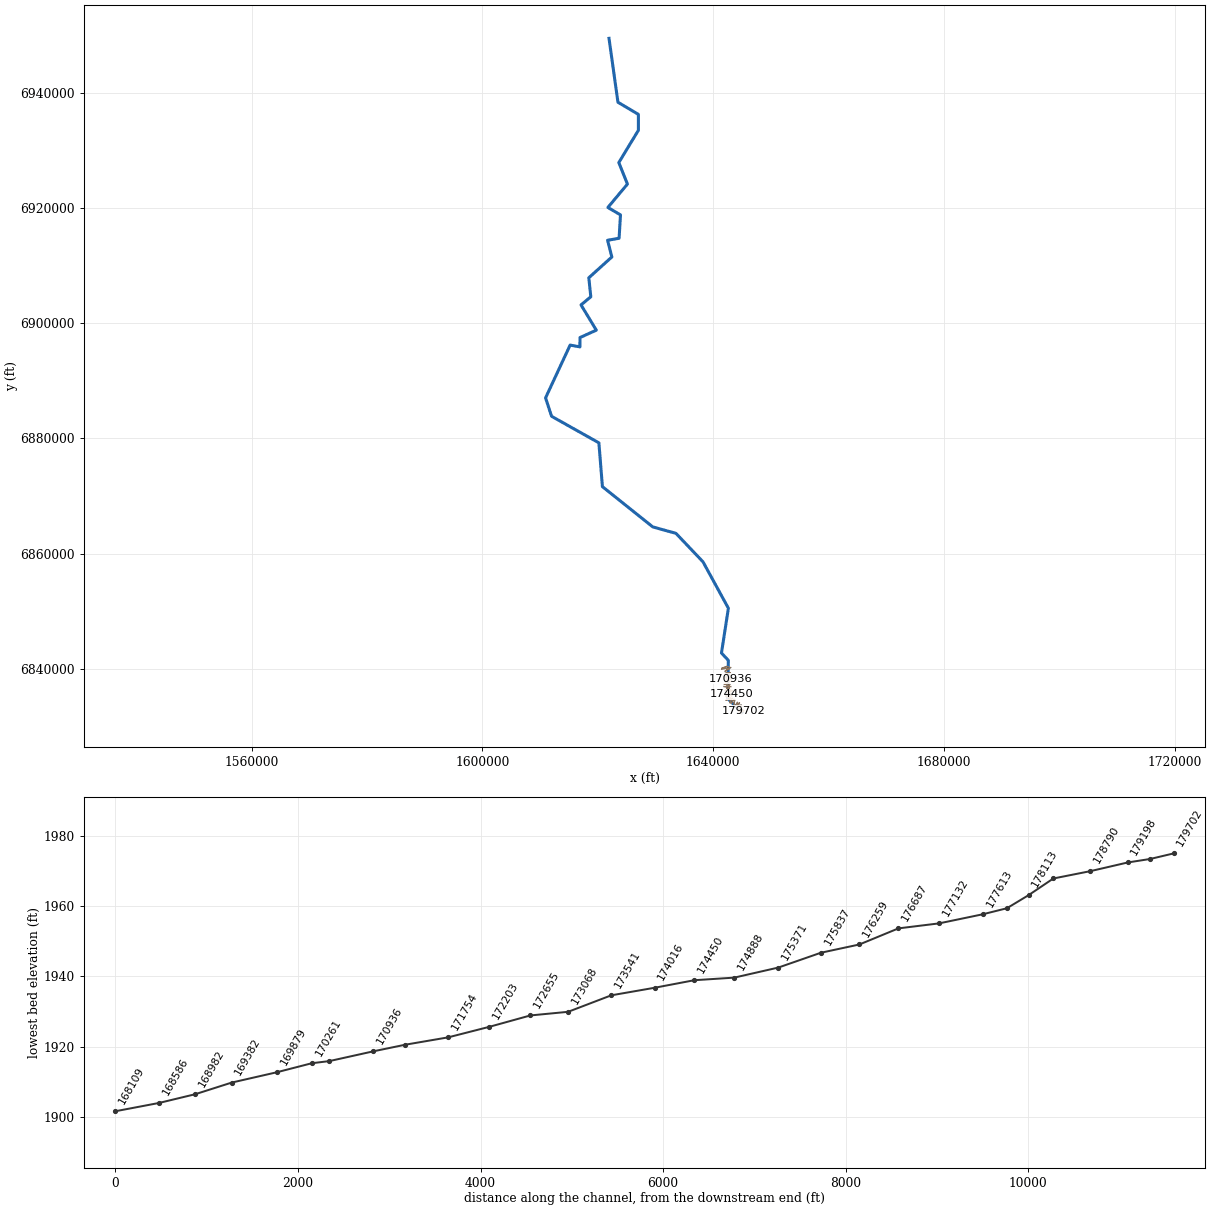
--- Deadman Creek.prj (project) ---

Proj Title=Deadman Creek Base Level Engineering
Current Plan=p01
Default Exp/Contr=0.3,0.1
English Units
Geom File=g01
Flow File=f01
Plan File=p01
BEGIN DESCRIPTION:
Deadman Creek
END DESCRIPTION:

--- Deadman Creek.p01 (plan) ---

Plan Title=Multiple Run
Short Identifier=Multiple
Geom File=g01
Flow File=f01
Subcritical Flow
K Sum by GR= 0
Std Step Tol= 0.01
Critical Tol= 0.01
Num of Std Step Trials= 20
Max Error Tol= 0.3
Flow Tol Ratio= 0.001
Split Flow NTrial= 30
Split Flow Tol= 0.02
Split Flow Ratio= 0.02
Log Output Level= 0
Friction Slope Method= 1
Unsteady Friction Slope Method= 2
Unsteady Bridges Friction Slope Method= 1
Parabolic Critical Depth
Global Vel Dist=  1 , 1 , 1
Global Log Level= 0
CheckData=True
Encroach Param= -1, 0, 0, 0
BEGIN DESCRIPTION:
Multiple Run
END DESCRIPTION:

--- Deadman Creek.f01 (steady flow) ---

Flow Title=Multiple
Number of Profiles=7
Profile Names=10-year,25-year,50-year,1pct_min,100-year,1pct_plu,500-year
River Rch & RM= Deadman Creek,Reach-1,179702
     205     279     338     204     407     811     597
River Rch & RM= Deadman Creek,Reach-1,179445
     269     372     456     279     557    1112     841
River Rch & RM= Deadman Creek,Reach-1,176259
     355     499     619     382     762    1520    1170
River Rch & RM= Deadman Creek,Reach-1,171284
     397     560     697     432     861    1719    1332
River Rch & RM= Deadman Creek,Reach-1,168982
     600     866    1094     686    1369    2732    2176
River Rch & RM= Deadman Creek,Reach-1,164996
     844    1235    1575     996    1988    3966    3211
River Rch & RM= Deadman Creek,Reach-1,158904
    1223    1816    2339    1494    2980    5946    4904
River Rch & RM= Deadman Creek,Reach-1,152393
    1233    1829    2355    1503    2998    5982    4926
River Rch & RM= Deadman Creek,Reach-1,150079
    1585    2370    3068    1967    3925    7831    6510
River Rch & RM= Deadman Creek,Reach-1,144041
    1699    2542    3291    2110    4210    8400    6983
River Rch & RM= Deadman Creek,Reach-1,139143
    1993    2992    3883    2495    4977    9931    8288
River Rch & RM= Deadman Creek,Reach-1,132945
    2400    3634    4745    3065    6115   12200   10295
River Rch & RM= Deadman Creek,Reach-1,129135
    2451    3709    4838    3122    6230   12430   10471
River Rch & RM= Deadman Creek,Reach-1,120906
    2433    3675    4788    3086    6157   12285   10321
River Rch & RM= Deadman Creek,Reach-1,117485
    2536    3830    4991    3217    6418   12806   10758
River Rch & RM= Deadman Creek,Reach-1,108291
    2759    4172    5441    3509    7002   13971   11752
River Rch & RM= Deadman Creek,Reach-1,100641
    2859    4320    5630    3628    7238   14442   12127
River Rch & RM= Deadman Creek,Reach-1,92732
    2941    4439    5781    3723    7428   14820   12424
River Rch & RM= Deadman Creek,Reach-1,87866
    3145    4735    6158    3959    7900   15763   13168
River Rch & RM= Deadman Creek,Reach-1,81529
    3099    4654    6043    3878    7738   15440   12852
River Rch & RM= Deadman Creek,Reach-1,75641
    3101    4654    6041    3876    7734   15431   12835
River Rch & RM= Deadman Creek,Reach-1,70837
    3457    5199    6758    4341    8661   17281   14406
River Rch & RM= Deadman Creek,Reach-1,66259
    3447    5181    6731    4322    8623   17204   14328
River Rch & RM= Deadman Creek,Reach-1,63491
    3471    5214    6772    4346    8672   17303   14401
River Rch & RM= Deadman Creek,Reach-1,61236
    3626    5449    7079    4545    9068   18093   15063
River Rch & RM= Deadman Creek,Reach-1,53764
    3641    5471    7107    4561    9101   18160   15114
River Rch & RM= Deadman Creek,Reach-1,52383
    3650    5478    7110    4560    9099   18154   15085
River Rch & RM= Deadman Creek,Reach-1,47431
    3649    5472    7099    4551    9080   18116   15037
River Rch & RM= Deadman Creek,Reach-1,43171
    4968    7491    9757    6277   12524   24989   20882
River Rch & RM= Deadman Creek,Reach-1,38086
    4971    7490    9752    6271   12512   24965   20842
River Rch & RM= Deadman Creek,Reach-1,32014
    4981    7503    9767    6279   12529   24999   20863
River Rch & RM= Deadman Creek,Reach-1,27793
    4963    7472    9723    6248   12466   24874   20741
River Rch & RM= Deadman Creek,Reach-1,24556
    6185    9348   12201    7862   15688   31301   26237
River Rch & RM= Deadman Creek,Reach-1,24110
    6183    9339   12185    7849   15661   31248   26171
River Rch & RM= Deadman Creek,Reach-1,20536
    6209    9377   12232    7879   15720   31366   26263
River Rch & RM= Deadman Creek,Reach-1,20110
    6201    9357   12200    7853   15669   31264   26147
River Rch & RM= Deadman Creek,Reach-1,17238
    6261    9451   12325    7936   15834   31593   26434
River Rch & RM= Deadman Creek,Reach-1,12439
    6285    9484   12365    7959   15881   31687   26499
River Rch & RM= Deadman Creek,Reach-1,7062
    6547    9884   12891    8301   16562   33045   27650
Boundary for River Rch & Prof#=Deadman Creek,Reach-1,1
Up Type=0
Dn Type=3
Dn Slope=0.0018
Boundary for River Rch & Prof#=Deadman Creek,Reach-1,2
Up Type=0
Dn Type=3
Dn Slope=0.0018
Boundary for River Rch & Prof#=Deadman Creek,Reach-1,3
Up Type=0
Dn Type=3
Dn Slope=0.0018
Boundary for River Rch & Prof#=Deadman Creek,Reach-1,4
Up Type=0
Dn Type=3
Dn Slope=0.0018
Boundary for River Rch & Prof#=Deadman Creek,Reach-1,5
Up Type=0
Dn Type=3
Dn Slope=0.0018
Boundary for River Rch & Prof#=Deadman Creek,Reach-1,6
Up Type=0
Dn Type=3
Dn Slope=0.0018
Boundary for River Rch & Prof#=Deadman Creek,Reach-1,7
Up Type=0
Dn Type=3
Dn Slope=0.0018

--- Deadman Creek.g01 (geometry) ---

Geom Title=Existing Conditions

River Reach=Deadman Creek,Reach-1
Reach XY= 30
      1645005.00      6832438.00      1642506.92      6834893.98
      1642647.78      6841487.69      1641454.70      6842762.88
      1642653.04      6850532.12      1638249.54      6858590.45
      1633565.01      6863527.38      1629548.95      6864646.16
      1620812.81      6871631.81      1620201.45      6879236.53
      1611998.92      6883846.13      1610955.00      6887038.00
      1615215.47      6896197.83      1616907.47      6895893.45
      1616924.60      6897508.17      1619752.94      6898793.85
      1617105.38      6903172.85      1618799.72      6904585.29
      1618458.61      6907886.50      1622452.75      6911493.93
      1621708.54      6914386.53      1623703.38      6914744.03
      1623946.91      6918794.08      1621762.23      6920087.69
      1625152.94      6924143.85      1623656.21      6927877.49
      1627055.00      6933488.00      1627047.19      6936244.19
      1623506.86      6938343.77      1621955.00      6949438.00

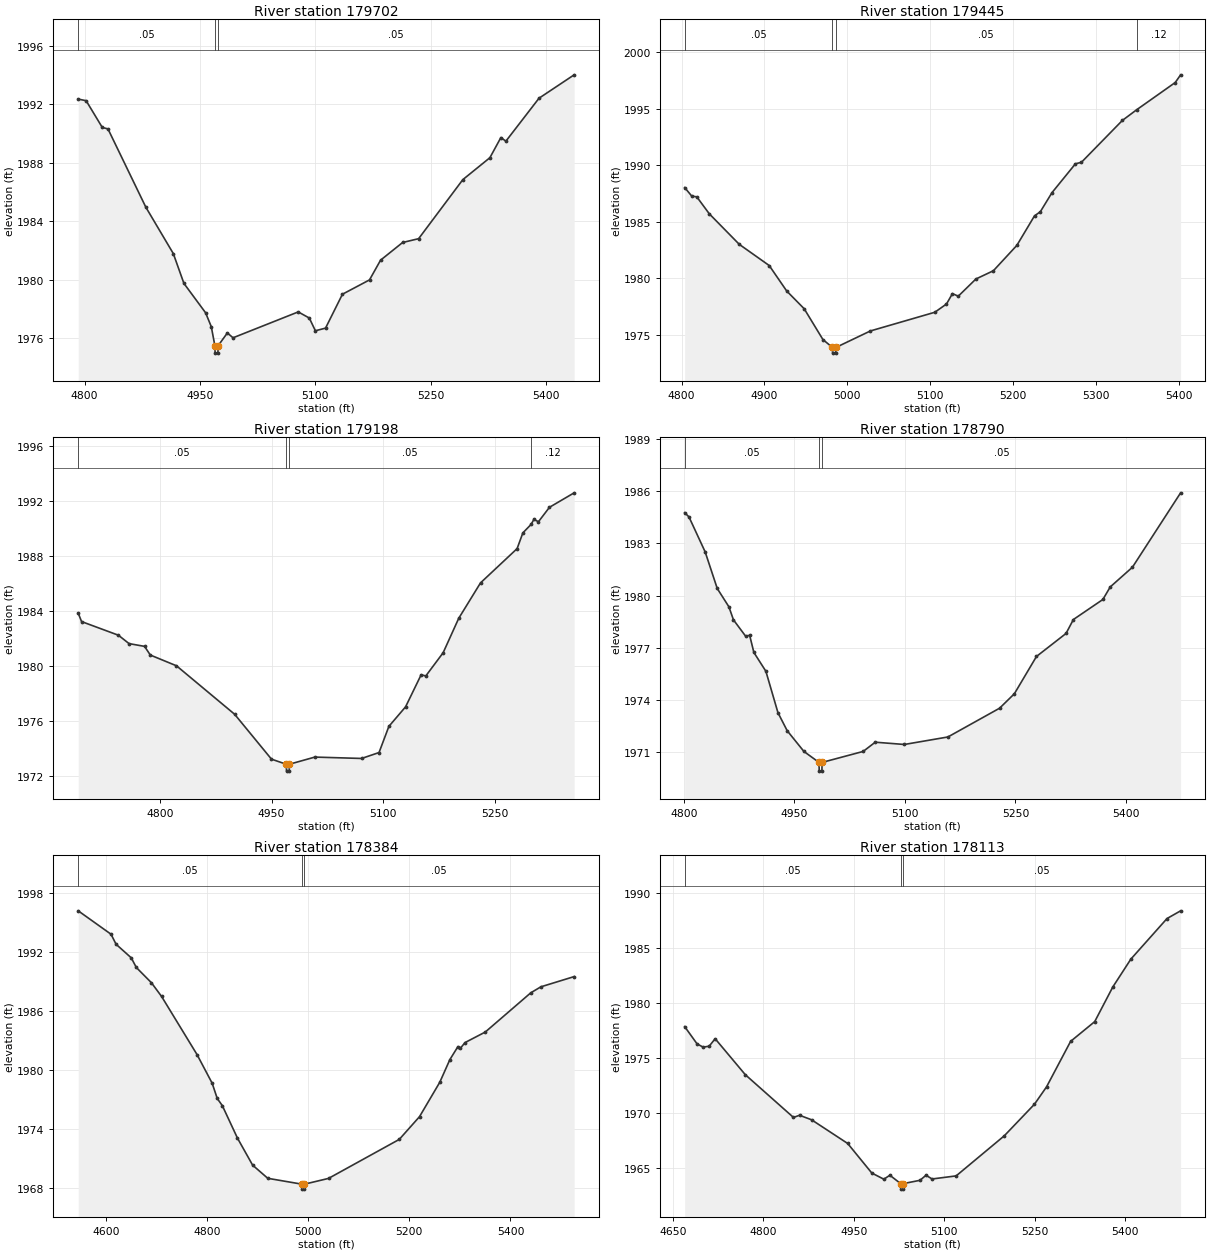
Type RM Length L Ch R = 1,179702,257,257,257
BEGIN DESCRIPTION:
Deadman Creek 246.0
END DESCRIPTION:
XS GIS Cut Line= 3
      1644861.94      6832286.63      1645005.15      6832442.86
      1645278.59      6832778.80
#Sta/Elev= 30
  4791.6 1992.35  4801.9 1992.24  4822.9 1990.41  4830.3 1990.31  4879.6 1984.95
  4915.3 1981.78  4929.1 1979.74  4957.3 1977.73  4964.7 1976.78  4969.4 1975.47
  4969.7 1974.97  4973.3 1974.97  4973.5 1975.47  4985.6 1976.35  4993.0 1976.02
  5077.8 1977.79  5092.2 1977.37  5100.1 1976.50  5113.3 1976.68  5135.3 1979.00
  5170.5 1979.98  5184.9 1981.33  5213.6 1982.54  5234.4 1982.80  5291.9 1986.84
  5327.1 1988.34  5341.4 1989.72  5347.9 1989.47  5391.0 1992.41  5436.7 1994.01
#Mann=3,-1,0
  4791.6    0.05       0  4969.4    0.03       0  4973.5    0.05       0
Bank Sta=4969.4,4973.5
Exp/Cntr=0.3,0.1

Type RM Length L Ch R = 1,179445,247,247,247
BEGIN DESCRIPTION:
Mapping XS 9f69b397
END DESCRIPTION:
XS GIS Cut Line= 3
      1644713.50      6832458.51      1644822.86      6832625.15
      1645108.93      6832903.41
#Sta/Elev= 30
  4803.8 1988.02  4812.4 1987.26  4818.4 1987.20  4833.5 1985.70  4869.7 1983.00
  4905.8 1981.13  4926.9 1978.88  4948.0 1977.31  4970.6 1974.59  4982.1 1973.89
  4982.3 1973.39  4985.9 1973.39  4986.2 1973.89  5027.9 1975.35  5105.6 1977.00
  5119.7 1977.73  5126.9 1978.65  5133.9 1978.42  5155.2 1979.94  5176.3 1980.67
  5204.6 1982.91  5225.9 1985.52  5232.9 1985.88  5247.0 1987.57  5275.3 1990.12
  5282.5 1990.25  5331.9 1993.95  5349.1 1994.89  5395.7 1997.30  5402.2 1997.98
#Mann=4,-1,0
  4803.8    0.05       0  4982.1    0.05       0  4986.2    0.05       0
  5349.1    0.12       0
Bank Sta=4982.1,4986.2
Exp/Cntr=0.3,0.1

Type RM Length L Ch R = 1,179198,408,408,408
BEGIN DESCRIPTION:
Mapping XS 0b207a60
END DESCRIPTION:
XS GIS Cut Line= 3
      1644475.67      6832581.25      1644671.58      6832811.07
      1644967.26      6833022.00
#Sta/Elev= 30
  4690.7 1983.86  4695.2 1983.25  4744.6 1982.26  4758.9 1981.65  4779.7 1981.45
  4787.4 1980.82  4822.5 1980.04  4900.5 1976.52  4949.9 1973.26  4969.8 1972.89
  4970.1 1972.39  4973.7 1972.39  4973.9 1972.89  5008.1 1973.41  5070.8 1973.31
  5094.2 1973.74  5107.4 1975.64  5129.8 1977.06  5150.7 1979.39  5156.9 1979.30
  5180.2 1980.99  5201.1 1983.49  5230.3 1986.06  5279.4 1988.55  5287.1 1989.69
  5298.2 1990.31  5301.9 1990.67  5308.0 1990.50  5322.8 1991.55  5355.9 1992.60
#Mann=4,-1,0
  4690.7    0.05       0  4969.8    0.05       0  4973.9    0.05       0
  5298.2    0.12       0
Bank Sta=4969.8,4973.9
Exp/Cntr=0.3,0.1

Type RM Length L Ch R = 1,178790,406,406,406
BEGIN DESCRIPTION:
Mapping XS fa1fc0e7
END DESCRIPTION:
XS GIS Cut Line= 3
      1644212.00      6832961.77      1644471.91      6833099.26
      1644850.31      6833119.97
#Sta/Elev= 30
  4801.1 1984.76  4806.9 1984.52  4828.9 1982.51  4845.3 1980.41  4861.1 1979.36
  4867.3 1978.61  4883.7 1977.68  4889.3 1977.72  4895.0 1976.74  4911.3 1975.66
  4927.7 1973.28  4940.2 1972.25  4962.9 1971.06  4983.4 1970.43  4983.7 1969.93
  4987.3 1969.93  4987.6 1970.43  5043.3 1971.06  5059.7 1971.59  5099.2 1971.46
  5158.3 1971.89  5228.4 1973.54  5248.5 1974.37  5278.5 1976.51  5318.6 1977.83
  5328.6 1978.63  5368.6 1979.78  5378.6 1980.50  5408.7 1981.63  5474.1 1985.90
#Mann=3,-1,0
  4801.1    0.05       0  4983.4    0.03       0  4987.6    0.05       0
Bank Sta=4983.4,4987.6
Exp/Cntr=0.3,0.1

Type RM Length L Ch R = 1,178384,271,271,271
BEGIN DESCRIPTION:
Mapping XS 03f95a40
END DESCRIPTION:
XS GIS Cut Line= 2
      1643950.14      6833421.36      1644930.73      6833449.59
#Sta/Elev= 30
  4545.0 1996.15  4609.9 1993.77  4619.9 1992.75  4649.9 1991.37  4659.9 1990.39
  4689.9 1988.83  4709.9 1987.44  4780.0 1981.53  4810.0 1978.61  4820.0 1977.06
  4830.0 1976.34  4860.0 1973.03  4890.0 1970.28  4920.0 1968.94  4987.9 1968.34
  4988.2 1967.84  4991.9 1967.84  4992.2 1968.34  5040.1 1968.93  5180.1 1972.90
  5220.1 1975.21  5260.2 1978.71  5280.2 1981.02  5296.1 1982.34  5301.1 1982.18
  5310.2 1982.75  5350.2 1983.82  5440.2 1987.81  5460.2 1988.42  5526.0 1989.46
#Mann=3,-1,0
  4545.0    0.05       0  4987.9    0.05       0  4992.2    0.05       0
Bank Sta=4987.9,4992.2
Exp/Cntr=0.3,0.1

Type RM Length L Ch R = 1,178113,238,238,238
BEGIN DESCRIPTION:
Mapping XS dddc5324
END DESCRIPTION:
XS GIS Cut Line= 3
      1644074.42      6833709.55      1644396.57      6833705.79
      1644897.57      6833711.44
#Sta/Elev= 30
  4669.2 1977.85  4689.8 1976.28  4699.8 1975.99  4709.8 1976.07  4719.8 1976.75
  4769.8 1973.49  4849.8 1969.61  4859.8 1969.81  4879.8 1969.40  4939.8 1967.25
  4979.8 1964.57  4999.8 1964.01  5009.8 1964.37  5027.7 1963.61  5028.0 1963.11
  5031.7 1963.11  5032.0 1963.61  5059.8 1963.91  5069.8 1964.37  5079.8 1964.03
  5119.8 1964.31  5199.8 1967.95  5249.8 1970.81  5269.8 1972.38  5309.8 1976.51
  5349.8 1978.30  5379.8 1981.44  5409.8 1983.97  5469.8 1987.65  5492.4 1988.35
#Mann=3,-1,0
  4669.2    0.05       0  5027.7    0.05       0  5032.0    0.05       0
Bank Sta=5027.7,5032
Exp/Cntr=0.3,0.1

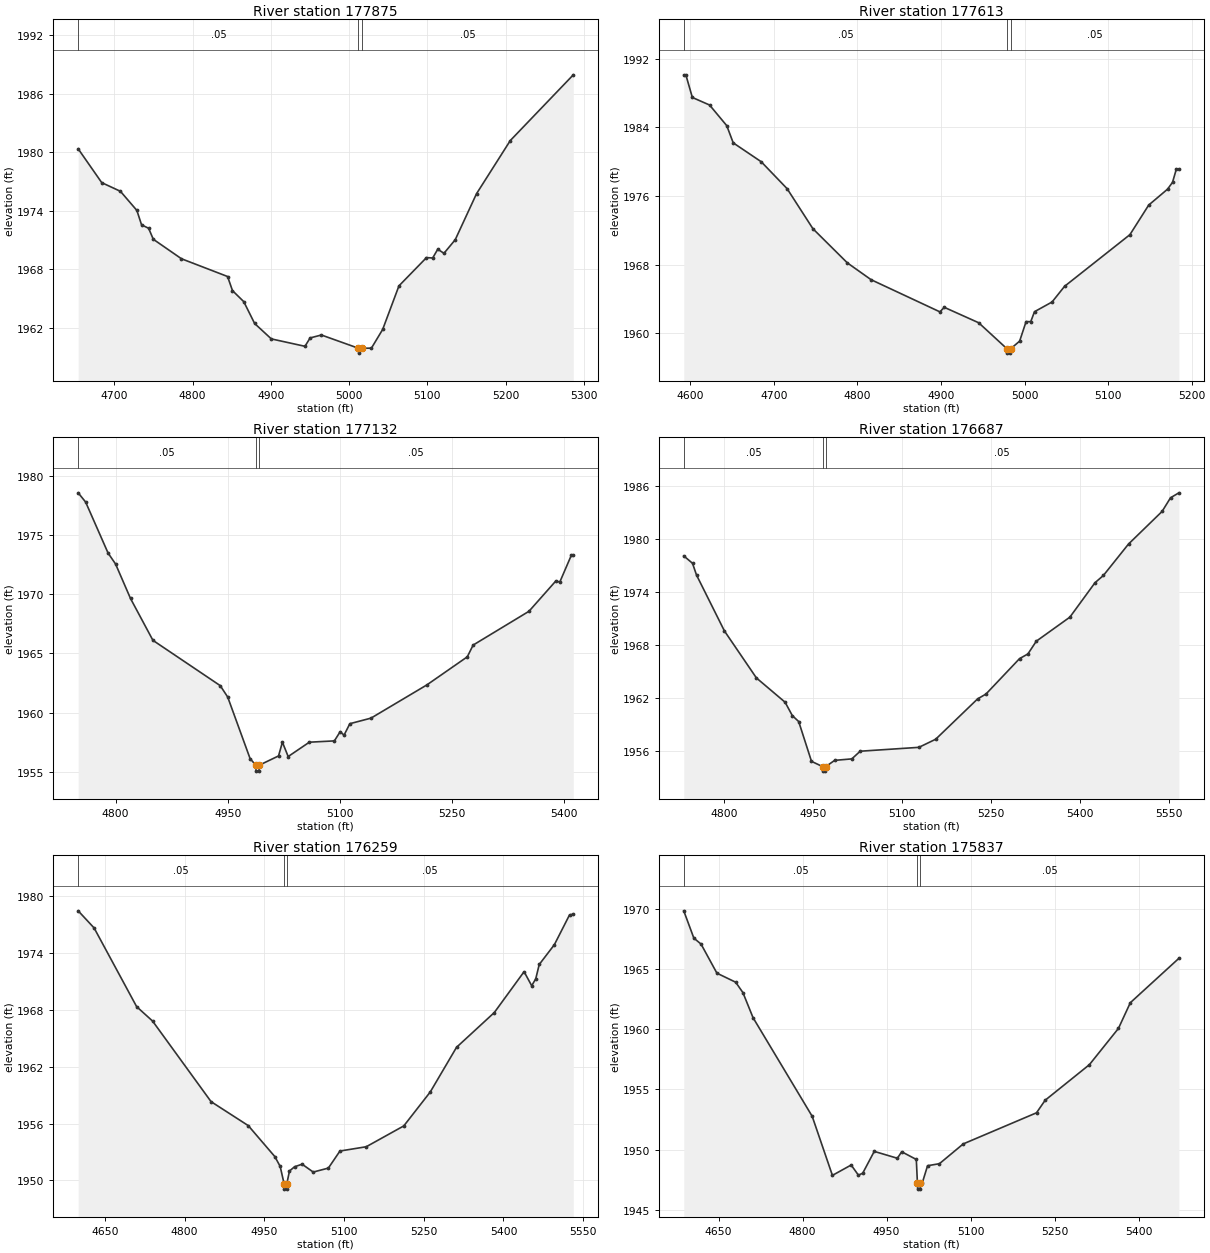
Type RM Length L Ch R = 1,177875,262,262,262
BEGIN DESCRIPTION:
Mapping XS b9e16337
END DESCRIPTION:
XS GIS Cut Line= 3
      1644050.02      6833709.58      1644206.32      6833815.04
      1644551.49      6834094.55
#Sta/Elev= 30
  4653.9 1980.34  4684.0 1976.87  4707.9 1975.98  4728.9 1974.02  4734.9 1972.54
  4743.9 1972.19  4749.9 1971.06  4785.9 1969.06  4844.8 1967.24  4851.1 1965.79
  4865.5 1964.66  4879.4 1962.42  4900.7 1960.84  4943.7 1960.08  4950.3 1960.94
  4964.7 1961.24  5012.1 1959.88  5012.4 1959.38  5016.4 1959.88  5028.6 1959.89
  5043.0 1961.81  5063.8 1966.28  5099.0 1969.18  5106.9 1969.14  5113.4 1970.04
  5121.3 1969.62  5135.7 1971.01  5162.9 1975.73  5206.1 1981.19  5286.6 1987.93
#Mann=3,-1,0
  4653.9    0.05       0  5012.1    0.05       0  5016.4    0.05       0
Bank Sta=5012.1,5016.4
Exp/Cntr=0.3,0.1

Type RM Length L Ch R = 1,177613,481,481,481
BEGIN DESCRIPTION:
Deadman Creek 242.0
END DESCRIPTION:
XS GIS Cut Line= 3
      1644005.01      6833638.03      1644105.00      6834038.00
      1644205.02      6834188.04
#Sta/Elev= 30
  4592.1 1990.12  4594.6 1990.12  4602.4 1987.48  4623.0 1986.60  4643.6 1984.19
  4651.3 1982.19  4684.8 1979.99  4715.8 1976.85  4746.7 1972.18  4787.9 1968.20
  4816.3 1966.24  4898.7 1962.49  4903.9 1963.02  4945.1 1961.22  4979.0 1958.18
  4979.3 1957.68  4983.1 1957.68  4983.3 1958.18  4994.1 1959.08  5001.8 1961.35
  5007.4 1961.35  5011.9 1962.51  5032.9 1963.64  5047.9 1965.47  5126.1 1971.49
  5148.6 1974.94  5171.1 1976.79  5177.1 1977.59  5181.7 1979.15  5184.7 1979.15
#Mann=3,-1,0
  4592.1    0.05       0  4979.0    0.05       0  4983.3    0.05       0
Bank Sta=4979,4983.3
Exp/Cntr=0.3,0.1

Type RM Length L Ch R = 1,177132,445,445,445
BEGIN DESCRIPTION:
Deadman Creek 241.0
END DESCRIPTION:
XS GIS Cut Line= 3
      1643655.00      6833888.03      1643655.00      6834138.00
      1643755.01      6834538.02
#Sta/Elev= 30
  4749.9 1978.55  4759.9 1977.77  4789.9 1973.47  4799.9 1972.55  4819.9 1969.64
  4849.9 1966.11  4939.9 1962.29  4949.9 1961.33  4979.9 1956.13  4987.6 1955.58
  4987.9 1955.08  4991.8 1955.08  4992.1 1955.58  5017.9 1956.36  5023.1 1957.52
  5030.8 1956.31  5059.1 1957.52  5092.6 1957.63  5100.4 1958.41  5105.5 1958.11
  5113.3 1959.08  5141.6 1959.55  5216.3 1962.35  5270.4 1964.72  5278.2 1965.71
  5352.9 1968.56  5389.0 1971.13  5394.1 1971.02  5409.6 1973.29  5412.2 1973.29
#Mann=3,-1,0
  4749.9    0.05       0  4987.6    0.05       0  4992.1    0.05       0
Bank Sta=4987.6,4992.1
Exp/Cntr=0.3,0.1

Type RM Length L Ch R = 1,176687,428,428,428
BEGIN DESCRIPTION:
Deadman Creek 240.0
END DESCRIPTION:
XS GIS Cut Line= 3
      1643205.02      6834088.04      1643305.00      6834338.00
      1643705.00      6834738.00
#Sta/Elev= 30
  4731.4 1978.09  4746.2 1977.25  4752.9 1975.92  4800.0 1969.57  4853.9 1964.24
  4902.3 1961.48  4914.5 1959.96  4925.2 1959.29  4946.8 1954.77  4966.0 1954.16
  4966.4 1953.66  4970.3 1953.66  4970.6 1954.16  4985.8 1954.88  5014.8 1955.05
  5028.9 1955.92  5127.9 1956.36  5156.2 1957.28  5226.9 1961.86  5241.0 1962.41
  5297.6 1966.43  5311.7 1966.96  5325.9 1968.41  5382.5 1971.14  5424.9 1975.05
  5439.0 1975.87  5481.4 1979.44  5538.0 1983.14  5552.2 1984.69  5566.3 1985.25
#Mann=3,-1,0
  4731.4    0.05       0  4966.0    0.05       0  4970.6    0.05       0
Bank Sta=4966,4970.6
Exp/Cntr=0.3,0.1

Type RM Length L Ch R = 1,176259,422,422,422
BEGIN DESCRIPTION:
Deadman Creek 239.0
END DESCRIPTION:
XS GIS Cut Line= 3
      1642955.00      6834138.03      1642955.00      6834538.00
      1643355.02      6834888.01
#Sta/Elev= 30
  4599.9 1978.44  4629.9 1976.63  4709.9 1968.33  4739.9 1966.81  4849.9 1958.31
  4919.9 1955.78  4969.9 1952.51  4979.9 1951.48  4987.6 1949.58  4987.9 1949.08
  4991.9 1949.08  4992.2 1949.58  4997.4 1950.99  5007.0 1951.44  5021.2 1951.71
  5042.1 1950.88  5070.6 1951.30  5092.4 1953.10  5141.8 1953.55  5212.5 1955.75
  5262.3 1959.33  5311.7 1964.04  5382.8 1967.71  5438.8 1972.02  5453.1 1970.54
  5460.7 1971.26  5467.3 1972.78  5495.8 1974.87  5524.3 1978.01  5531.4 1978.08
#Mann=3,-1,0
  4599.9    0.05       0  4987.6    0.05       0  4992.2    0.05       0
Bank Sta=4987.6,4992.2
Exp/Cntr=0.3,0.1

Type RM Length L Ch R = 1,175837,466,466,466
BEGIN DESCRIPTION:
Deadman Creek 238.0
END DESCRIPTION:
XS GIS Cut Line= 3
      1642255.03      6834588.01      1642655.00      6834688.00
      1643055.02      6834938.01
#Sta/Elev= 30
  4587.9 1969.81  4605.9 1967.55  4618.8 1967.05  4647.1 1964.64  4680.6 1963.89
  4693.5 1963.03  4711.6 1960.95  4817.2 1952.77  4853.3 1947.87  4886.8 1948.73
  4899.7 1947.89  4907.4 1948.05  4928.0 1949.86  4969.3 1949.29  4977.0 1949.83
  5003.1 1949.19  5005.1 1947.23  5005.6 1946.73  5010.1 1946.73  5010.5 1947.23
  5013.7 1947.24  5023.2 1948.67  5044.4 1948.84  5086.9 1950.48  5217.7 1953.06
  5233.1 1954.10  5312.1 1957.05  5364.0 1960.06  5385.2 1962.19  5471.9 1965.87
#Mann=3,-1,0
  4587.9    0.05       0  5005.1    0.05       0  5010.5    0.05       0
Bank Sta=5005.1,5010.5
Exp/Cntr=0.3,0.1

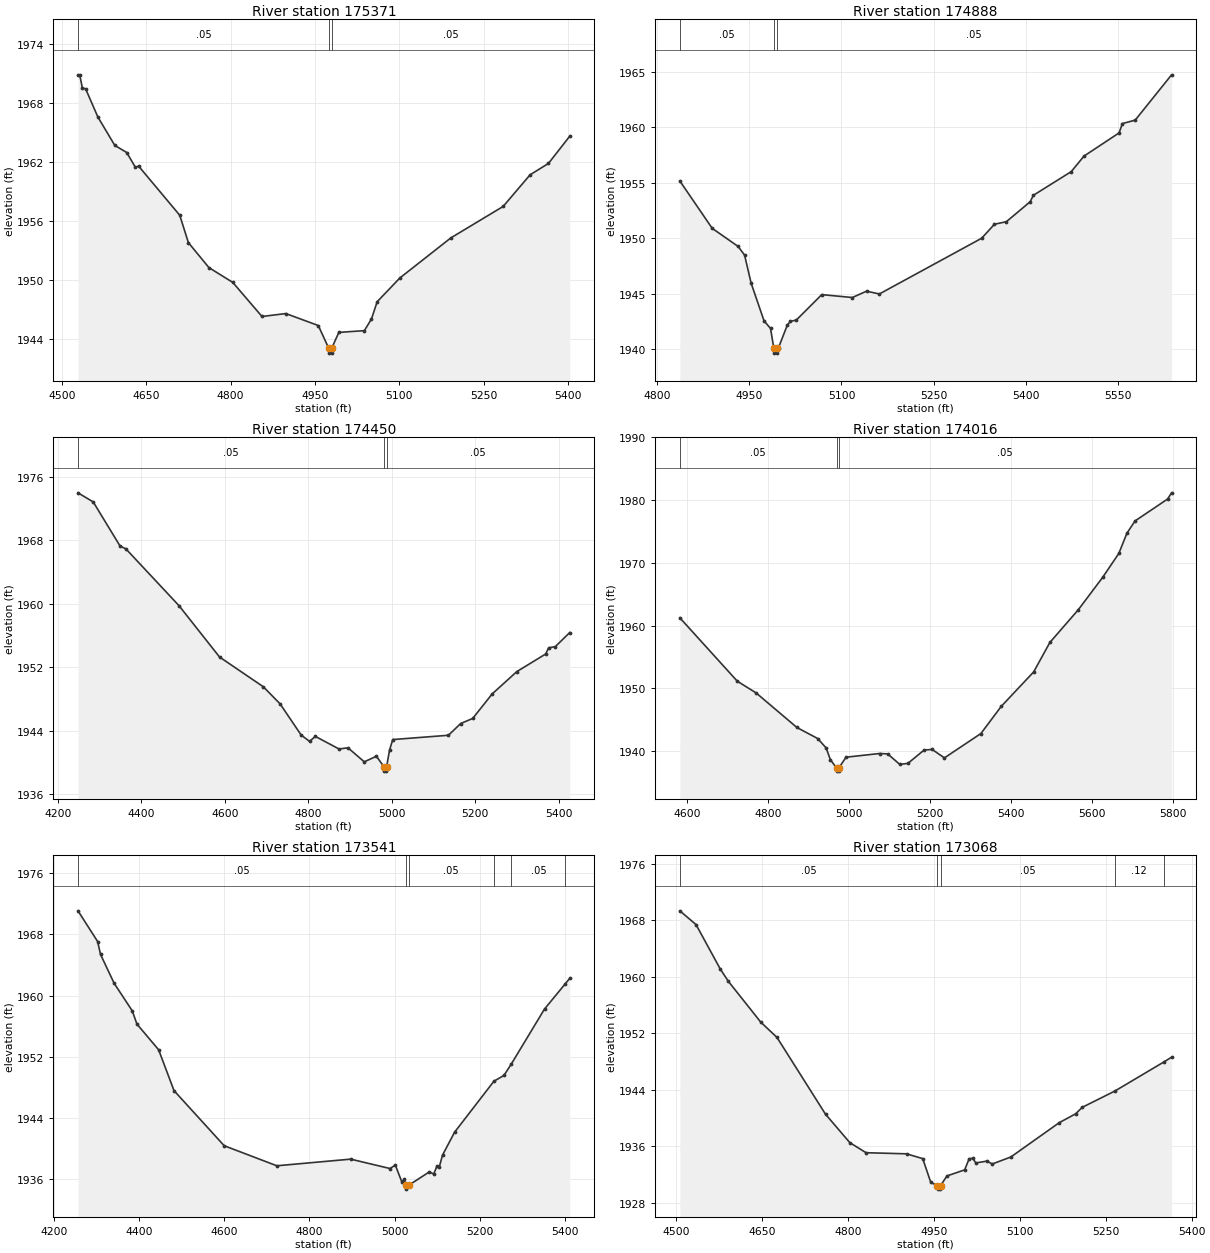
Type RM Length L Ch R = 1,175371,483,483,483
BEGIN DESCRIPTION:
Deadman Creek 237.0
END DESCRIPTION:
XS GIS Cut Line= 3
      1642204.99      6835288.01      1642605.00      6835038.00
      1643004.98      6834988.00
#Sta/Elev= 30
  4528.5 1970.86  4531.5 1970.86  4536.2 1969.54  4542.1 1969.43  4563.9 1966.56
  4594.0 1963.67  4615.2 1962.95  4630.5 1961.45  4636.4 1961.56  4709.5 1956.56
  4724.9 1953.77  4761.4 1951.23  4803.9 1949.72  4855.8 1946.25  4898.2 1946.55
  4956.0 1945.33  4974.5 1943.02  4975.0 1942.52  4979.5 1942.52  4979.9 1943.02
  4992.5 1944.63  5038.0 1944.81  5050.6 1946.00  5060.7 1947.75  5101.0 1950.17
  5191.7 1954.25  5284.9 1957.46  5332.8 1960.68  5365.5 1961.84  5403.3 1964.61
#Mann=3,-1,0
  4528.5    0.05       0  4974.5    0.05       0  4979.9    0.05       0
Bank Sta=4974.5,4979.9
Exp/Cntr=0.3,0.1

Type RM Length L Ch R = 1,174888,438,438,438
BEGIN DESCRIPTION:
Deadman Creek 236.0
END DESCRIPTION:
XS GIS Cut Line= 3
      1642454.98      6835538.01      1642605.00      6835488.00
      1643221.86      6835309.15
#Sta/Elev= 30
  4836.9 1955.17  4889.6 1950.90  4931.8 1949.27  4942.3 1948.49  4952.9 1945.97
  4974.0 1942.56  4984.5 1941.89  4989.7 1940.16  4990.1 1939.66  4994.7 1939.66
  4995.1 1940.16  4997.6 1940.16  5011.8 1942.18  5017.0 1942.53  5026.3 1942.63
  5067.9 1944.93  5117.7 1944.67  5140.8 1945.24  5161.7 1944.99  5328.2 1950.01
  5349.0 1951.27  5368.4 1951.50  5407.2 1953.30  5412.4 1953.88  5474.0 1956.01
  5494.8 1957.41  5551.9 1959.50  5557.3 1960.34  5578.1 1960.65  5637.3 1964.73
#Mann=3,-1,0
  4836.9    0.05       0  4989.7    0.05       0  4995.1    0.05       0
Bank Sta=4989.7,4995.1
Exp/Cntr=0.3,0.1

Type RM Length L Ch R = 1,174450,434,434,434
BEGIN DESCRIPTION:
Deadman Creek 235.0
END DESCRIPTION:
XS GIS Cut Line= 3
      1642105.04      6835887.99      1642855.00      6835788.00
      1643241.32      6835619.15
#Sta/Elev= 30
  4248.5 1974.00  4285.0 1972.85  4349.3 1967.29  4363.2 1966.94  4490.6 1959.77
  4587.7 1953.30  4692.4 1949.56  4732.7 1947.40  4783.2 1943.47  4803.3 1942.67
  4817.2 1943.30  4873.9 1941.71  4895.4 1941.86  4934.5 1940.09  4963.5 1940.80
  4982.2 1939.42  4982.6 1938.92  4987.2 1938.92  4987.7 1939.42  4995.0 1941.57
  5002.6 1942.90  5136.1 1943.44  5165.4 1944.92  5194.2 1945.56  5241.0 1948.66
  5299.8 1951.46  5368.9 1953.68  5376.2 1954.46  5392.3 1954.62  5426.7 1956.39
#Mann=3,-1,0
  4248.5    0.05       0  4982.2    0.05       0  4987.7    0.05       0
Bank Sta=4982.2,4987.7
Exp/Cntr=0.3,0.1

Type RM Length L Ch R = 1,174016,475,475,475
BEGIN DESCRIPTION:
Deadman Creek 234.0
END DESCRIPTION:
XS GIS Cut Line= 3
      1642305.04      6835988.01      1642705.00      6836088.00
      1643505.03      6836088.00
#Sta/Elev= 30
  4583.1 1961.23  4724.8 1951.12  4771.2 1949.25  4871.7 1943.74  4923.2 1941.97
  4943.8 1940.47  4954.1 1938.63  4969.4 1937.28  4969.8 1936.78  4974.5 1936.78
  4975.0 1937.28  4992.8 1939.00  5075.4 1939.59  5095.4 1939.53  5125.4 1937.85
  5145.4 1938.02  5185.4 1940.15  5205.4 1940.23  5235.4 1938.89  5325.4 1942.78
  5375.4 1947.10  5455.4 1952.60  5495.4 1957.30  5565.4 1962.51  5625.4 1967.67
  5665.4 1971.50  5685.4 1974.73  5705.4 1976.68  5785.4 1980.16  5795.4 1981.16
#Mann=3,-1,0
  4583.1    0.05       0  4969.4    0.03       0  4975.0    0.05       0
Bank Sta=4969.4,4975
Exp/Cntr=0.3,0.1

Type RM Length L Ch R = 1,173541,473,473,473
BEGIN DESCRIPTION:
Deadman Creek 233.0
END DESCRIPTION:
XS GIS Cut Line= 3
      1642155.04      6836138.02      1642855.00      6836388.00
      1643255.03      6836287.99
#Sta/Elev= 30
  4256.1 1971.10  4302.2 1967.08  4309.1 1965.38  4341.0 1961.61  4383.5 1958.00
  4394.6 1956.26  4445.6 1952.89  4481.7 1947.54  4599.6 1940.32  4723.3 1937.69
  4896.9 1938.56  4989.3 1937.33  5001.9 1937.78  5017.4 1935.53  5022.6 1935.90
  5027.5 1935.13  5027.9 1934.63  5033.1 1935.13  5081.8 1936.89  5092.1 1936.61
  5099.9 1937.68  5105.0 1937.50  5112.7 1939.08  5141.1 1942.09  5233.5 1948.77
  5257.1 1949.53  5274.8 1951.06  5352.4 1958.23  5401.1 1961.53  5411.7 1962.25
#Mann=6,-1,0
  4256.1    0.05       0  5027.5    0.05       0  5033.1    0.05       0
  5233.5    0.12       0  5274.8    0.05       0  5401.1    0.12       0
Bank Sta=5027.5,5033.1
Exp/Cntr=0.3,0.1

Type RM Length L Ch R = 1,173068,413,413,413
BEGIN DESCRIPTION:
Deadman Creek 232.0
END DESCRIPTION:
XS GIS Cut Line= 3
      1642105.01      6836238.01      1642455.00      6836588.00
      1642805.03      6836688.01
#Sta/Elev= 30
  4505.9 1969.36  4534.2 1967.41  4576.6 1961.11  4590.7 1959.37  4647.3 1953.59
  4675.6 1951.43  4760.4 1940.55  4802.9 1936.52  4831.2 1935.10  4901.9 1934.94
  4930.2 1934.26  4944.3 1930.89  4955.6 1930.44  4956.1 1929.94  4960.8 1929.94
  4961.3 1930.44  4972.6 1931.81  5003.5 1932.67  5011.3 1934.25  5017.8 1934.29
  5023.0 1933.65  5042.5 1933.91  5051.6 1933.50  5084.1 1934.49  5168.6 1939.35
  5197.2 1940.60  5208.9 1941.53  5265.8 1943.83  5351.2 1947.94  5364.9 1948.63
#Mann=5,-1,0
  4505.9    0.05       0  4955.6    0.05       0  4961.3    0.05       0
  5265.8    0.12       0  5351.2    0.05       0
Bank Sta=4955.6,4961.3
Exp/Cntr=0.3,0.1

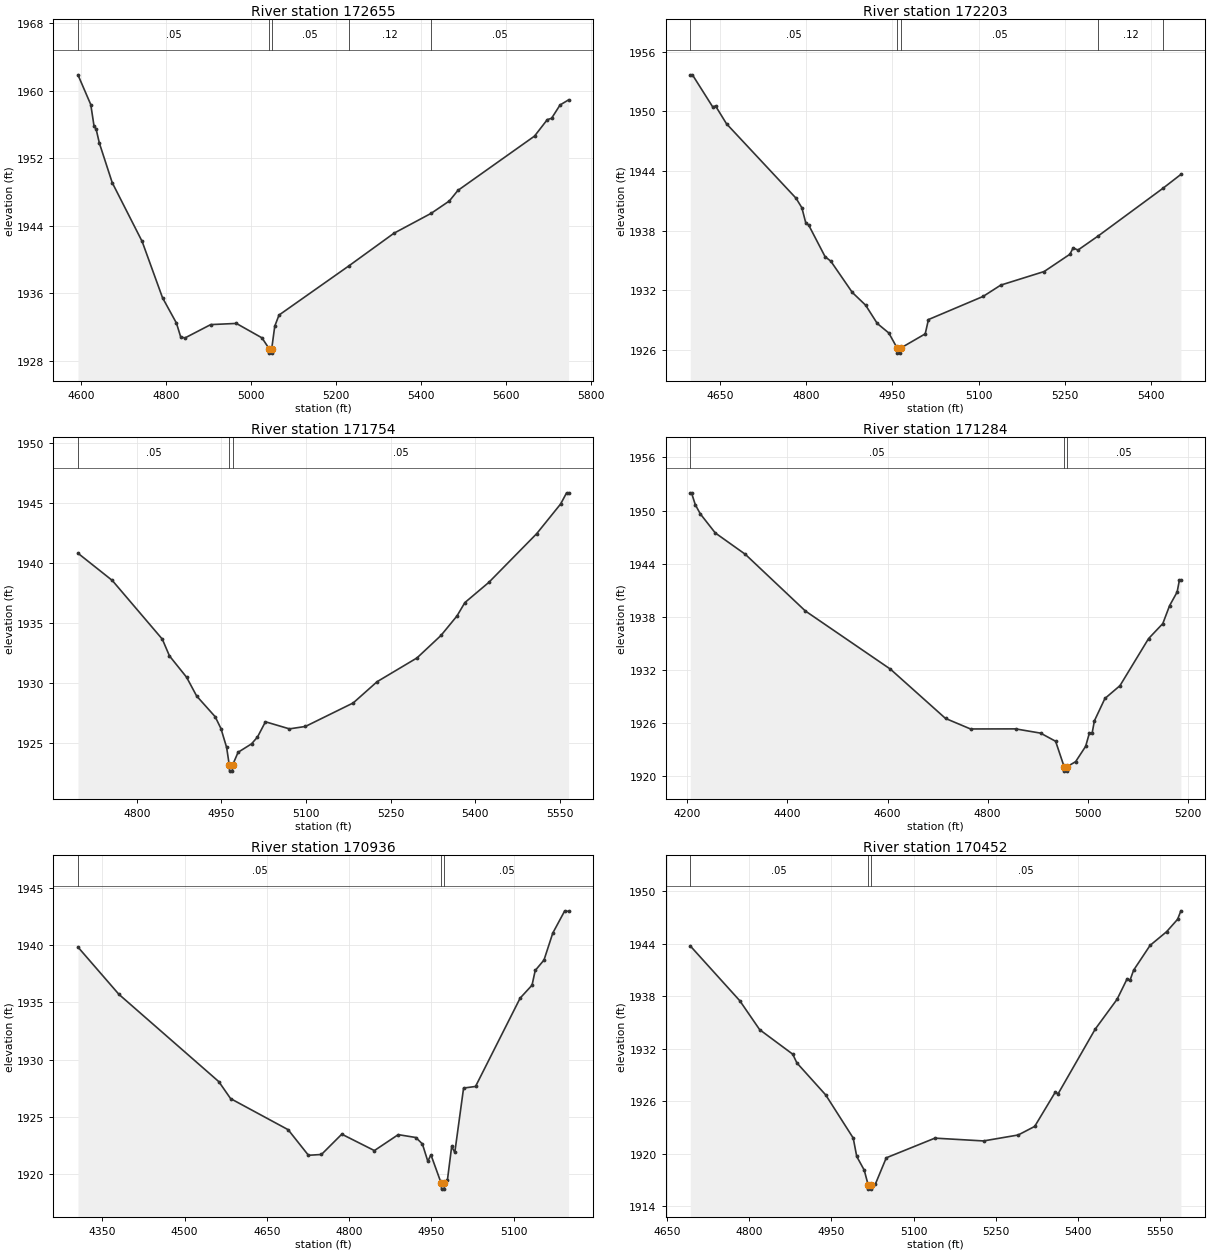
Type RM Length L Ch R = 1,172655,452,452,452
BEGIN DESCRIPTION:
Deadman Creek 231.0
END DESCRIPTION:
XS GIS Cut Line= 3
      1641905.04      6836938.00      1642305.00      6836888.00
      1643054.96      6836938.00
#Sta/Elev= 30
  4592.4 1961.89  4622.6 1958.36  4630.2 1955.84  4635.2 1955.45  4642.8 1953.80
  4673.0 1949.12  4743.5 1942.14  4791.4 1935.48  4824.2 1932.47  4834.2 1930.83
  4844.3 1930.71  4904.8 1932.29  4965.2 1932.43  5025.5 1930.72  5042.7 1929.41
  5043.2 1928.91  5048.0 1928.91  5048.4 1929.41  5055.6 1932.10  5065.6 1933.42
  5229.5 1939.23  5336.2 1943.12  5423.8 1945.48  5466.5 1946.94  5486.6 1948.19
  5667.0 1954.63  5697.0 1956.58  5707.1 1956.74  5727.1 1958.32  5747.1 1958.92
#Mann=5,-1,0
  4592.4    0.05       0  5042.7    0.05       0  5048.4    0.05       0
  5229.5    0.12       0  5423.8    0.05       0
Bank Sta=5042.7,5048.4
Exp/Cntr=0.3,0.1

Type RM Length L Ch R = 1,172203,449,449,449
BEGIN DESCRIPTION:
Deadman Creek 230.0
END DESCRIPTION:
XS GIS Cut Line= 3
      1641952.51      6837337.93      1642355.00      6837288.00
      1642755.01      6837087.99
#Sta/Elev= 30
  4598.8 1953.69  4602.6 1953.69  4637.7 1950.47  4642.8 1950.55  4661.8 1948.76
  4782.7 1941.26  4792.8 1940.30  4799.6 1938.77  4804.6 1938.56  4833.1 1935.38
  4843.1 1934.92  4880.5 1931.77  4903.6 1930.49  4923.8 1928.65  4943.9 1927.69
  4958.5 1926.16  4959.0 1925.66  4963.8 1925.66  4964.3 1926.16  5007.2 1927.60
  5012.8 1929.04  5107.8 1931.37  5138.5 1932.51  5214.0 1933.88  5258.7 1935.62
  5264.3 1936.26  5272.7 1936.04  5308.3 1937.48  5420.6 1942.27  5451.6 1943.66
#Mann=5,-1,0
  4598.8    0.05       0  4958.5    0.03       0  4964.3    0.05       0
  5308.3    0.12       0  5420.6    0.05       0
Bank Sta=4958.5,4964.3
Exp/Cntr=0.3,0.1

Type RM Length L Ch R = 1,171754,470,470,470
BEGIN DESCRIPTION:
Deadman Creek 229.0
END DESCRIPTION:
XS GIS Cut Line= 3
      1642204.98      6837738.00      1642505.00      6837688.00
      1642904.97      6837288.03
#Sta/Elev= 30
  4695.6 1940.83  4756.5 1938.56  4845.2 1933.67  4857.8 1932.28  4888.2 1930.50
  4906.0 1928.94  4938.9 1927.21  4949.1 1926.23  4959.2 1924.65  4963.9 1923.18
  4964.4 1922.68  4969.3 1922.68  4969.7 1923.18  4979.5 1924.25  5003.3 1924.95
  5013.9 1925.52  5028.0 1926.79  5070.5 1926.20  5098.8 1926.40  5183.6 1928.36
  5226.0 1930.13  5296.7 1932.11  5339.2 1933.98  5367.5 1935.60  5381.6 1936.72
  5424.0 1938.40  5508.9 1942.46  5551.3 1944.93  5561.9 1945.86  5565.4 1945.86
#Mann=3,-1,0
  4695.6    0.05       0  4963.9    0.05       0  4969.7    0.05       0
Bank Sta=4963.9,4969.7
Exp/Cntr=0.3,0.1

Type RM Length L Ch R = 1,171284,348,348,348
BEGIN DESCRIPTION:
Deadman Creek 228.0
END DESCRIPTION:
XS GIS Cut Line= 3
      1642055.00      6837938.00      1642855.00      6837938.00
      1643005.02      6837837.98
#Sta/Elev= 30
  4205.8 1952.01  4208.3 1952.01  4215.8 1950.68  4225.8 1949.64  4255.8 1947.48
  4315.8 1945.07  4435.8 1938.67  4605.8 1932.10  4715.8 1926.54  4765.8 1925.35
  4855.8 1925.36  4905.8 1924.88  4935.8 1923.96  4952.8 1921.09  4953.3 1920.59
  4958.2 1920.59  4958.7 1921.09  4975.8 1921.66  4995.8 1923.39  5003.3 1924.89
  5008.8 1924.89  5013.3 1926.27  5034.3 1928.79  5064.4 1930.24  5121.5 1935.55
  5150.0 1937.25  5163.5 1939.27  5178.6 1940.81  5183.1 1942.14  5186.1 1942.14
#Mann=3,-1,0
  4205.8    0.05       0  4952.8    0.05       0  4958.7    0.05       0
Bank Sta=4952.8,4958.7
Exp/Cntr=0.3,0.1

Type RM Length L Ch R = 1,170936,484,484,484
BEGIN DESCRIPTION:
Mapping XS b93543b9
END DESCRIPTION:
XS GIS Cut Line= 3
      1642290.57      6838049.95      1642778.22      6838131.61
      1643128.18      6838325.25
#Sta/Elev= 30
  4305.5 1939.82  4380.2 1935.70  4562.3 1928.09  4583.8 1926.61  4688.7 1923.90
  4725.7 1921.67  4749.4 1921.74  4786.5 1923.51  4845.9 1922.08  4889.4 1923.47
  4921.5 1923.22  4933.4 1922.66  4943.3 1921.15  4949.0 1921.71  4967.8 1919.22
  4968.3 1918.72  4973.2 1918.72  4973.7 1919.22  4979.1 1919.53  4986.8 1922.44
  4992.5 1921.92  5008.5 1927.53  5030.3 1927.67  5111.6 1935.37  5133.3 1936.50
  5139.1 1937.78  5155.1 1938.69  5171.1 1941.04  5192.9 1942.98  5199.9 1942.93
#Mann=3,-1,0
  4305.5    0.05       0  4967.8    0.05       0  4973.7    0.05       0
Bank Sta=4967.8,4973.7
Exp/Cntr=0.3,0.1

Type RM Length L Ch R = 1,170452,191,191,191
BEGIN DESCRIPTION:
Mapping XS 85bdde2f
END DESCRIPTION:
XS GIS Cut Line= 3
      1642298.84      6838421.27      1642746.78      6838379.60
      1643191.02      6838345.83
#Sta/Elev= 30
  4692.3 1943.74  4782.7 1937.47  4819.0 1934.16  4879.3 1931.36  4886.9 1930.36
  4939.5 1926.70  4989.7 1921.77  4996.1 1919.67  5009.8 1918.10  5016.9 1916.43
  5017.4 1915.93  5022.4 1915.93  5022.9 1916.43  5029.9 1916.47  5050.0 1919.51
  5138.8 1921.76  5227.5 1921.44  5290.8 1922.12  5320.9 1923.10  5358.6 1927.03
  5363.6 1926.83  5431.2 1934.21  5471.3 1937.64  5489.7 1939.99  5494.8 1939.80
  5501.4 1940.96  5531.5 1943.80  5561.6 1945.36  5581.7 1946.78  5587.7 1947.75
#Mann=3,-1,0
  4692.3    0.05       0  5016.9    0.05       0  5022.9    0.05       0
Bank Sta=5016.9,5022.9
Exp/Cntr=0.3,0.1

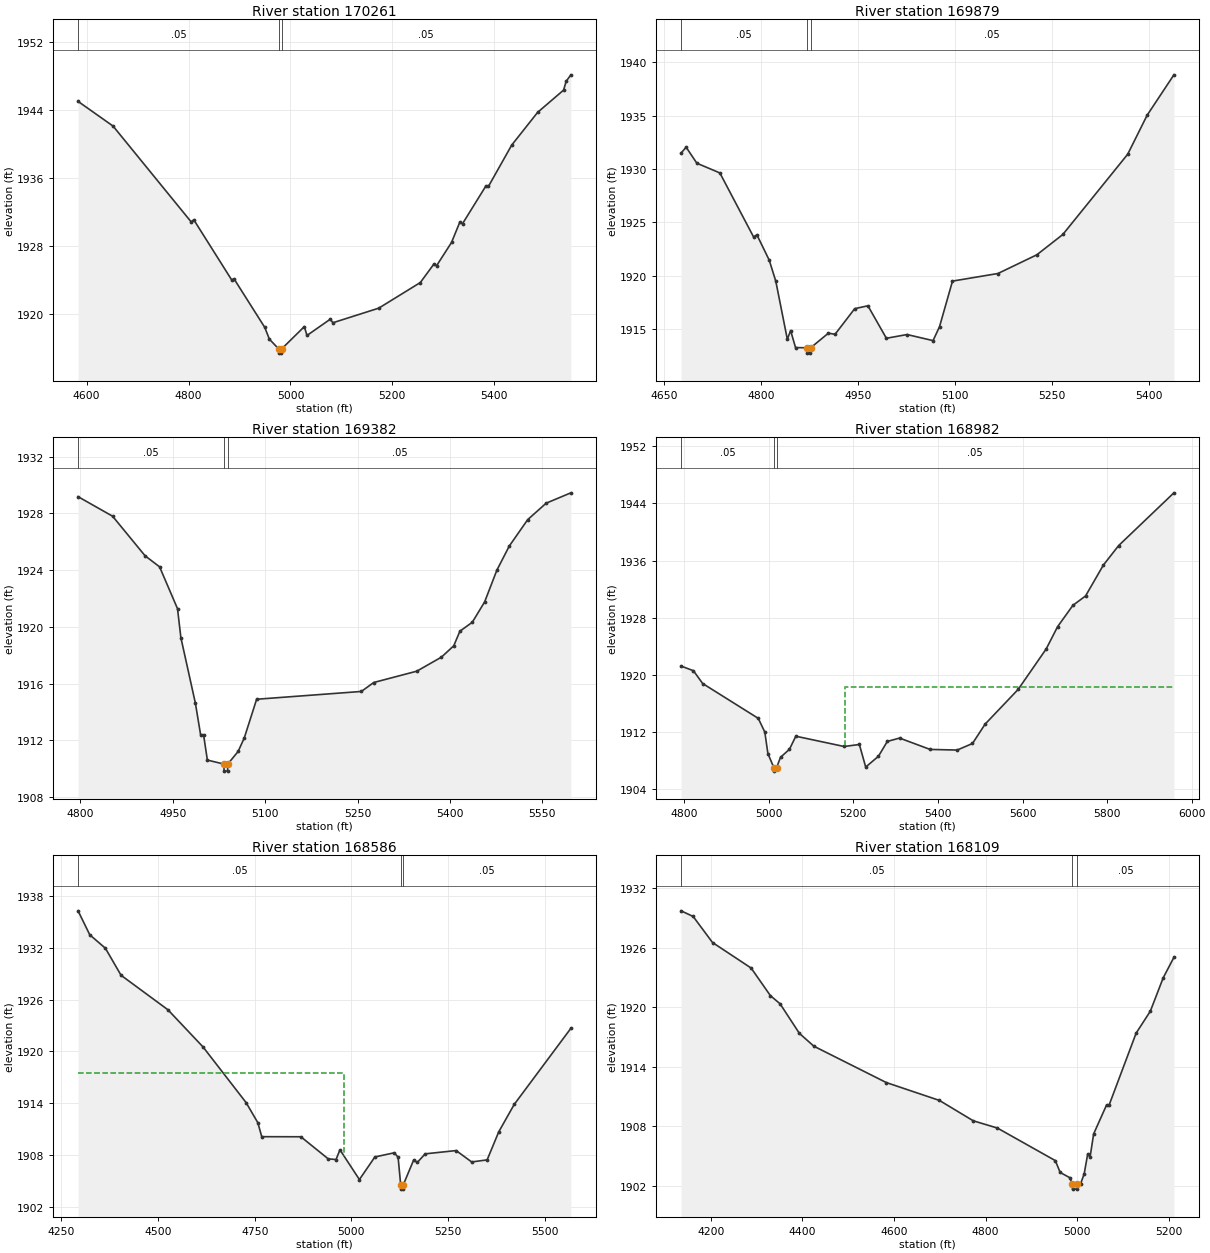
Type RM Length L Ch R = 1,170261,382,382,382
BEGIN DESCRIPTION:
Deadman Creek 226.0
END DESCRIPTION:
XS GIS Cut Line= 3
      1642241.58      6838621.79      1642663.44      6838567.10
      1643194.73      6838460.32
#Sta/Elev= 30
  4583.1 1945.00  4651.8 1942.09  4805.2 1930.79  4810.2 1931.05  4884.4 1923.98
  4889.5 1924.06  4949.6 1918.36  4958.6 1916.98  4976.8 1915.83  4977.3 1915.33
  4982.3 1915.33  4982.8 1915.83  5027.3 1918.46  5032.4 1917.41  5078.2 1919.33
  5083.3 1918.91  5173.3 1920.63  5254.9 1923.65  5281.7 1925.84  5286.8 1925.63
  5316.1 1928.37  5332.6 1930.79  5337.7 1930.58  5383.5 1935.02  5388.6 1934.98
  5434.3 1939.85  5485.2 1943.71  5536.1 1946.33  5541.2 1947.37  5550.4 1948.13
#Mann=3,-1,0
  4583.1    0.05       0  4976.8    0.03       0  4982.8    0.05       0
Bank Sta=4976.8,4982.8
Exp/Cntr=0.3,0.1

Type RM Length L Ch R = 1,169879,497,497,497
BEGIN DESCRIPTION:
Deadman Creek 225.0
END DESCRIPTION:
XS GIS Cut Line= 3
      1642291.01      6838994.19      1642606.15      6838934.29
      1643046.24      6838895.23
#Sta/Elev= 30
  4676.0 1931.49  4683.8 1932.04  4700.4 1930.54  4736.0 1929.63  4788.2 1923.64
  4793.3 1923.84  4812.4 1921.47  4822.6 1919.49  4840.4 1914.07  4845.5 1914.88
  4853.1 1913.29  4870.5 1913.27  4871.0 1912.77  4876.0 1912.77  4876.5 1913.27
  4904.0 1914.64  4914.2 1914.53  4944.7 1916.93  4965.1 1917.20  4993.7 1914.16
  5025.7 1914.51  5065.9 1913.94  5075.9 1915.24  5096.0 1919.51  5166.3 1920.22
  5226.5 1921.97  5266.7 1923.87  5367.1 1931.38  5397.2 1935.03  5438.6 1938.81
#Mann=3,-1,0
  4676.0    0.05       0  4870.5    0.03       0  4876.5    0.05       0
Bank Sta=4870.5,4876.5
Exp/Cntr=0.3,0.1

Type RM Length L Ch R = 1,169382,400,400,400
BEGIN DESCRIPTION:
Deadman Creek 224.0
END DESCRIPTION:
XS GIS Cut Line= 3
      1642171.28      6839259.82      1642358.83      6839339.58
      1642955.08      6839322.31
#Sta/Elev= 30
  4796.2 1929.18  4852.3 1927.80  4905.0 1925.01  4928.6 1924.23  4957.7 1921.28
  4963.2 1919.23  4986.8 1914.60  4995.2 1912.39  5000.0 1912.39  5006.2 1910.60
  5032.9 1910.32  5033.4 1909.82  5038.9 1909.82  5039.4 1910.32  5056.2 1911.21
  5066.2 1912.17  5086.2 1914.89  5256.3 1915.44  5276.3 1916.07  5346.3 1916.87
  5386.3 1917.86  5406.3 1918.66  5416.3 1919.69  5436.4 1920.32  5456.4 1921.75
  5476.4 1924.00  5496.4 1925.69  5526.4 1927.56  5556.4 1928.72  5596.5 1929.45
#Mann=3,-1,0
  4796.2    0.05       0  5032.9    0.05       0  5039.4    0.05       0
Bank Sta=5032.9,5039.4
Exp/Cntr=0.3,0.1

Type RM Length L Ch R = 1,168982,396,396,396
BEGIN DESCRIPTION:
Deadman Creek 223.0
END DESCRIPTION:
XS GIS Cut Line= 3
      1642074.87      6839608.75      1642270.21      6839715.54
      1643054.99      6840237.99
#Sta/Elev= 30
  4792.6 1921.22  4821.8 1920.57  4843.6 1918.78  4975.1 1913.90  4990.6 1911.98
  4997.9 1908.97  5011.9 1907.01  5012.4 1906.51  5018.4 1907.01  5027.8 1908.45
  5048.9 1909.57  5063.9 1911.40  5178.1 1909.96  5214.2 1910.24  5229.2 1907.08
  5259.3 1908.59  5280.3 1910.67  5309.3 1911.14  5381.4 1909.55  5445.6 1909.46
  5481.7 1910.38  5511.7 1913.10  5589.8 1917.96  5656.0 1923.62  5683.0 1926.74
  5719.1 1929.72  5749.1 1931.04  5791.2 1935.36  5827.3 1938.09  5958.0 1945.48
#Mann=3,-1,0
  4792.6    0.05       0  5011.9    0.03       0  5018.4    0.05       0
#XS Ineff=2,0
       0                 5180.00    0.00 1918.36
Permanent Ineff=
       F       F
Bank Sta=5011.9,5018.4
Exp/Cntr=0.3,0.1

Type RM Length L Ch R = 1,168586,477,477,477
BEGIN DESCRIPTION:
Deadman Creek 222.0
END DESCRIPTION:
XS GIS Cut Line= 3
      1641505.03      6839988.00      1642205.00      6840088.00
      1642771.37      6840074.95
#Sta/Elev= 30
  4293.5 1936.29  4323.8 1933.51  4364.2 1931.95  4404.6 1928.82  4525.8 1924.82
  4616.7 1920.50  4727.8 1914.06  4758.1 1911.73  4768.2 1910.11  4869.3 1910.10
  4940.0 1907.54  4960.2 1907.46  4970.3 1908.59  5020.6 1905.14  5060.6 1907.76
  5110.6 1908.24  5120.6 1907.73  5127.3 1904.53  5127.8 1904.03  5133.5 1904.03
  5134.0 1904.53  5160.6 1907.38  5170.6 1907.14  5190.6 1908.12  5270.6 1908.50
  5310.7 1907.18  5350.7 1907.42  5380.7 1910.67  5420.7 1913.85  5567.1 1922.67
#Mann=3,-1,0
  4293.5    0.05       0  5127.3    0.03       0  5134.0    0.05       0
#XS Ineff=2,0
    0.00 4980.00 1917.50               0
Permanent Ineff=
       F       F
Bank Sta=5127.3,5134
Exp/Cntr=0.3,0.1

Type RM Length L Ch R = 1,168109,449,449,449
BEGIN DESCRIPTION:
Deadman Creek 221.0
END DESCRIPTION:
XS GIS Cut Line= 3
      1641579.97      6840162.99      1642405.00      6840438.00
      1642604.98      6840388.00
#Sta/Elev= 30
  4135.1 1929.70  4161.5 1929.13  4203.7 1926.51  4288.0 1923.94  4330.1 1921.16
  4351.2 1920.34  4393.4 1917.36  4425.0 1916.07  4583.1 1912.41  4699.1 1910.61
  4772.9 1908.56  4825.6 1907.83  4952.1 1904.55  4962.6 1903.36  4983.7 1902.83
  4989.1 1902.18  4989.6 1901.68  4998.8 1901.68  4999.3 1902.18  5007.3 1902.22
  5015.1 1903.23  5022.8 1905.23  5028.0 1904.93  5035.7 1907.24  5064.0 1910.16
  5069.2 1910.11  5128.5 1917.39  5159.4 1919.59  5187.7 1922.97  5210.9 1925.01
#Mann=3,-1,0
  4135.1    0.05       0  4989.1    0.03       0  4999.3    0.05       0
Bank Sta=4989.1,4999.3
Exp/Cntr=0.3,0.1