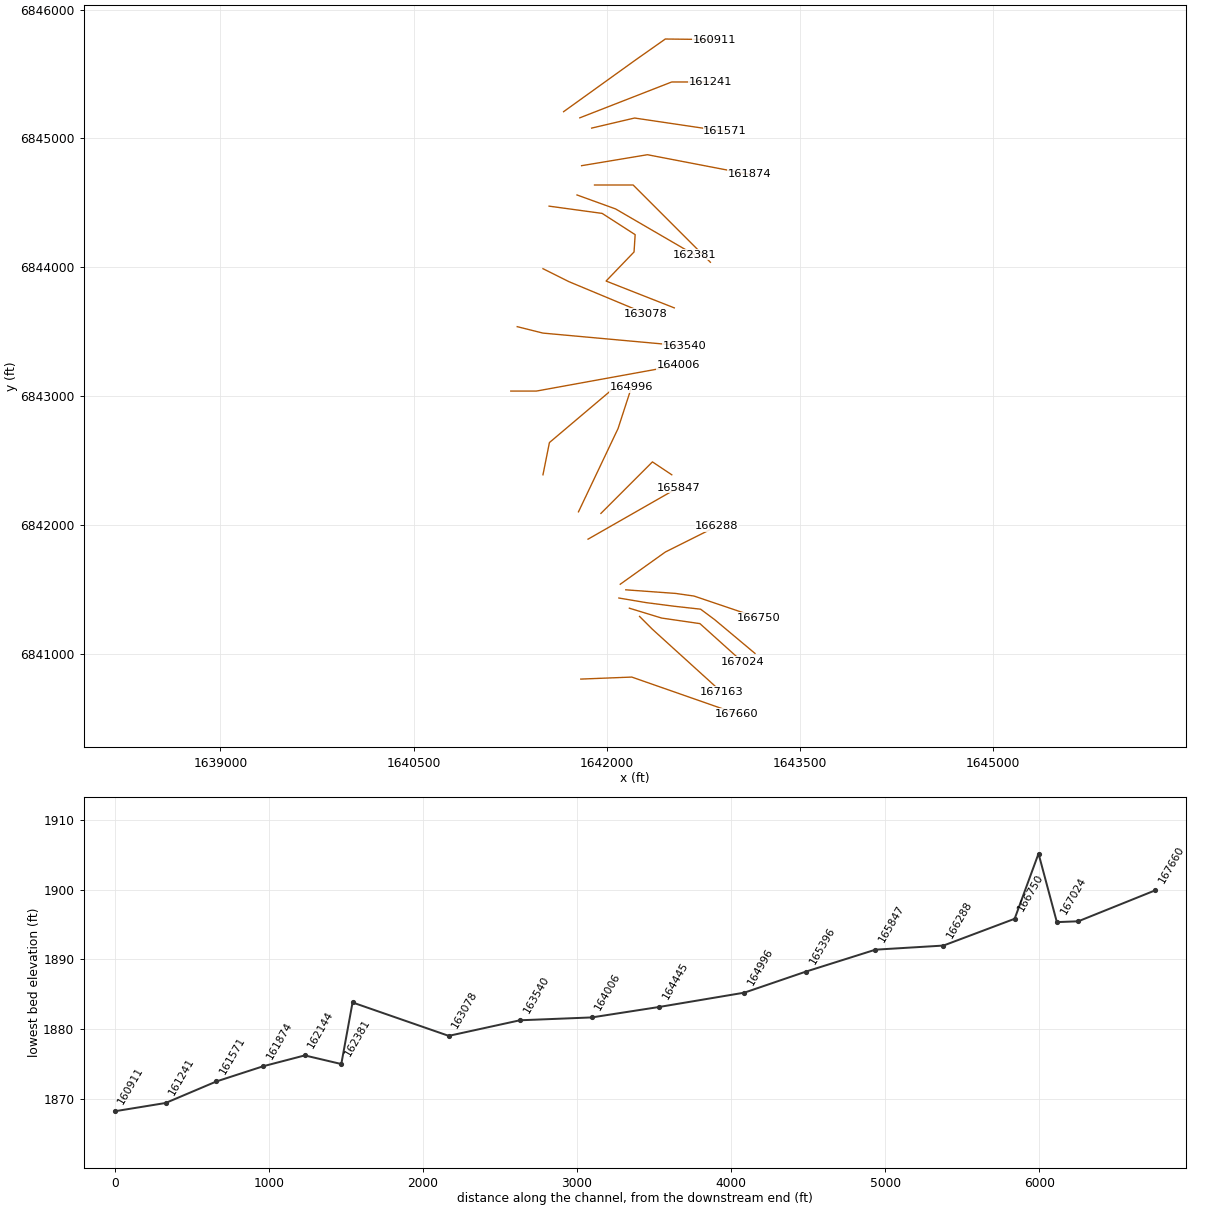
HEC-RAS study Deadman Creek.prj: Deadman Creek Base Level Engineering

--- Deadman Creek.g01 (geometry) --- (continued)

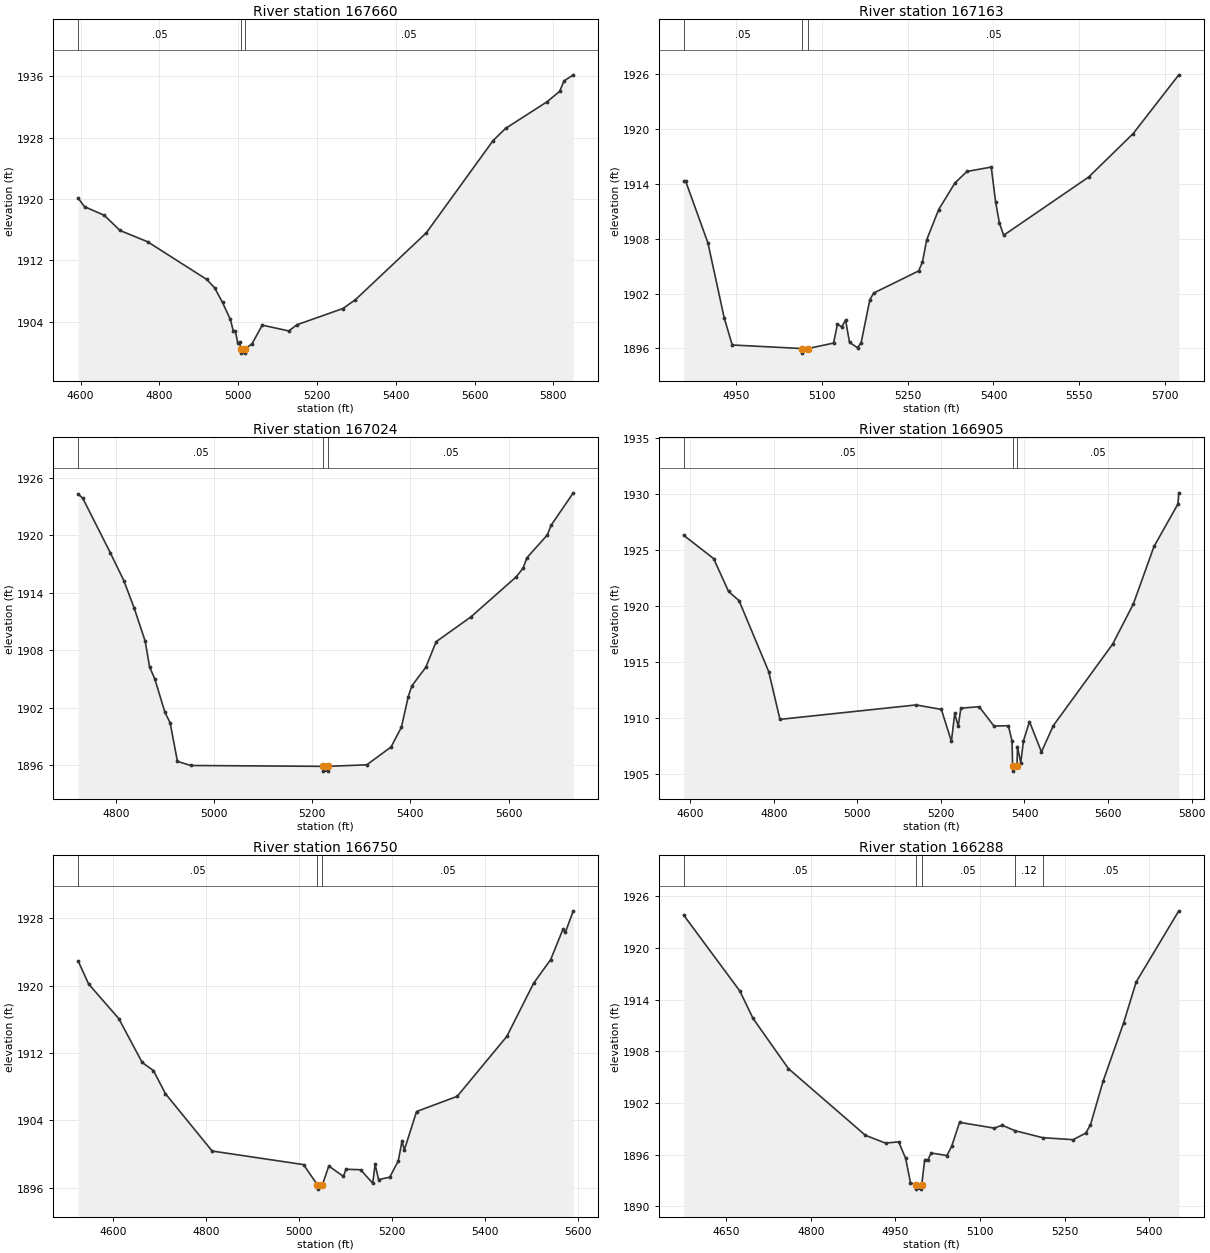
Type RM Length L Ch R = 1,167660,497,497,497
BEGIN DESCRIPTION:
Deadman Creek 220.0
END DESCRIPTION:
XS GIS Cut Line= 3
      1641798.87      6840801.48      1642194.69      6840817.10
      1643007.20      6840533.24
#Sta/Elev= 30
  4593.8 1920.10  4609.9 1919.00  4660.0 1917.88  4700.0 1915.90  4770.1 1914.43
  4920.2 1909.52  4940.2 1908.43  4960.2 1906.52  4980.2 1904.31  4987.6 1902.81
  4992.7 1902.81  4999.0 1901.21  5004.3 1901.36  5006.2 1900.42  5006.7 1899.92
  5016.1 1899.92  5016.6 1900.42  5035.3 1901.15  5061.1 1903.57  5128.5 1902.81
  5148.9 1903.61  5265.7 1905.73  5297.4 1906.87  5477.5 1915.59  5647.0 1927.61
  5678.8 1929.20  5784.7 1932.69  5816.1 1934.03  5827.1 1935.38  5850.6 1936.18
#Mann=3,-1,0
  4593.8    0.05       0  5006.2    0.03       0  5016.6    0.05       0
Bank Sta=5006.2,5016.6
Exp/Cntr=0.3,0.1

Type RM Length L Ch R = 1,167163,139,139,139
BEGIN DESCRIPTION:
Deadman Creek 219.0
END DESCRIPTION:
XS GIS Cut Line= 3
      1642255.03      6841287.97      1642355.00      6841188.00
      1642891.35      6840701.36
#Sta/Elev= 30
  4858.4 1914.26  4861.9 1914.26  4900.8 1907.52  4929.1 1899.37  4943.2 1896.38
  5065.2 1895.99  5065.7 1895.49  5075.6 1895.99  5120.4 1896.59  5127.2 1898.67
  5134.6 1898.35  5141.4 1899.10  5148.3 1896.66  5162.3 1896.08  5168.6 1896.63
  5183.9 1901.34  5190.7 1902.06  5269.1 1904.47  5275.8 1905.45  5283.3 1907.89
  5304.2 1911.18  5332.6 1914.08  5353.6 1915.34  5396.1 1915.82  5403.6 1912.05
  5410.3 1909.72  5417.8 1908.37  5566.4 1914.73  5644.2 1919.48  5724.0 1925.90
#Mann=3,-1,0
  4858.4    0.05       0  5065.2    0.03       0  5075.6    0.05       0
Bank Sta=5065.2,5075.6
Exp/Cntr=0.3,0.1

Type RM Length L Ch R = 1,167024,119,119,119
BEGIN DESCRIPTION:
Mapping XS 02125809
END DESCRIPTION:
XS GIS Cut Line= 4
      1642175.96      6841351.90      1642425.67      6841275.46
      1642723.83      6841232.13      1643055.09      6840934.00
#Sta/Elev= 30
  4723.5 1924.33  4732.9 1923.89  4789.3 1918.16  4816.6 1915.27  4837.5 1912.42
  4860.0 1908.95  4868.9 1906.26  4879.4 1905.02  4900.3 1901.50  4910.7 1900.43
  4925.6 1896.39  4952.6 1895.96  5221.2 1895.87  5221.7 1895.37  5231.2 1895.37
  5231.7 1895.87  5311.1 1896.03  5360.4 1897.88  5381.7 1899.96  5395.6 1903.16
  5403.0 1904.29  5431.4 1906.23  5452.4 1908.90  5523.4 1911.50  5615.3 1915.67
  5629.5 1916.59  5637.0 1917.66  5678.8 1920.06  5686.3 1921.05  5731.6 1924.46
#Mann=3,-1,0
  4723.5    0.05       0  5221.2    0.03       0  5231.7    0.05       0
Bank Sta=5221.2,5231.7
Exp/Cntr=0.3,0.1

Type RM Length L Ch R = 1,166905,155,155,155
BEGIN DESCRIPTION:
Mapping XS 72ddc36e
END DESCRIPTION:
XS GIS Cut Line= 6
      1642094.43      6841430.90      1642305.90      6841395.23
      1642522.51      6841367.20      1642728.93      6841344.26
      1642838.51      6841262.71      1643150.97      6841001.06
#Sta/Elev= 30
  4584.6 1926.31  4656.2 1924.23  4691.9 1921.29  4717.0 1920.47  4788.0 1914.12
  4814.9 1909.85  5140.7 1911.14  5201.1 1910.74  5225.2 1907.89  5233.1 1910.38
  5241.5 1909.22  5247.7 1910.85  5291.6 1910.98  5327.0 1909.25  5361.5 1909.28
  5370.2 1907.92  5371.6 1905.72  5372.1 1905.22  5382.1 1905.72  5383.3 1907.42
  5391.1 1905.96  5397.6 1907.93  5412.0 1909.65  5440.6 1906.94  5469.2 1909.30
  5611.0 1916.58  5660.5 1920.17  5709.9 1925.31  5767.2 1929.11  5769.3 1930.11
#Mann=3,-1,0
  4584.6    0.05       0  5371.6    0.05       0  5382.1    0.05       0
Bank Sta=5371.6,5382.1
Exp/Cntr=0.3,0.1

Type RM Length L Ch R = 1,166750,462,462,462
BEGIN DESCRIPTION:
Mapping XS f265a20e
END DESCRIPTION:
XS GIS Cut Line= 4
      1642147.88      6841494.62      1642535.25      6841466.58
      1642677.96      6841446.20      1643181.28      6841275.88
#Sta/Elev= 30
  4525.3 1922.92  4547.6 1920.20  4612.7 1916.07  4662.8 1910.88  4687.0 1909.92
  4712.9 1907.17  4813.2 1900.37  5009.6 1898.76  5039.5 1896.35  5040.0 1895.85
  5050.0 1896.35  5063.9 1898.59  5095.3 1897.36  5100.6 1898.21  5132.1 1898.15
  5158.2 1896.56  5163.5 1898.78  5170.8 1896.98  5194.9 1897.27  5213.1 1899.19
  5221.1 1901.51  5226.4 1900.53  5252.5 1905.06  5339.8 1906.86  5446.4 1913.97
  5504.0 1920.28  5540.7 1923.09  5566.9 1926.67  5572.1 1926.30  5589.2 1928.87
#Mann=3,-1,0
  4525.3    0.05       0  5039.5    0.05       0  5050.0    0.05       0
Bank Sta=5039.5,5050
Exp/Cntr=0.3,0.1

Type RM Length L Ch R = 1,166288,441,441,441
BEGIN DESCRIPTION:
Deadman Creek 217.0
END DESCRIPTION:
XS GIS Cut Line= 3
      1642105.04      6841538.03      1642455.00      6841788.00
      1642855.01      6841988.01
#Sta/Elev= 30
  4574.9 1923.80  4674.4 1914.99  4697.7 1911.82  4760.4 1905.99  4896.8 1898.25
  4932.5 1897.34  4955.8 1897.49  4968.1 1895.58  4976.7 1892.76  4986.2 1892.50
  4986.7 1892.00  4996.2 1892.00  4996.7 1892.50  5001.9 1895.42  5007.8 1895.42
  5013.4 1896.19  5041.3 1895.90  5049.7 1896.97  5063.7 1899.75  5125.2 1899.08
  5139.1 1899.42  5161.6 1898.79  5211.1 1897.97  5264.9 1897.74  5287.3 1898.50
  5295.7 1899.47  5318.0 1904.52  5354.4 1911.29  5376.7 1916.05  5452.2 1924.30
#Mann=5,-1,0
  4574.9    0.05       0  4986.2    0.05       0  4996.7    0.05       0
  5161.6    0.12       0  5211.1    0.05       0
Bank Sta=4986.2,4996.7
Exp/Cntr=0.3,0.1

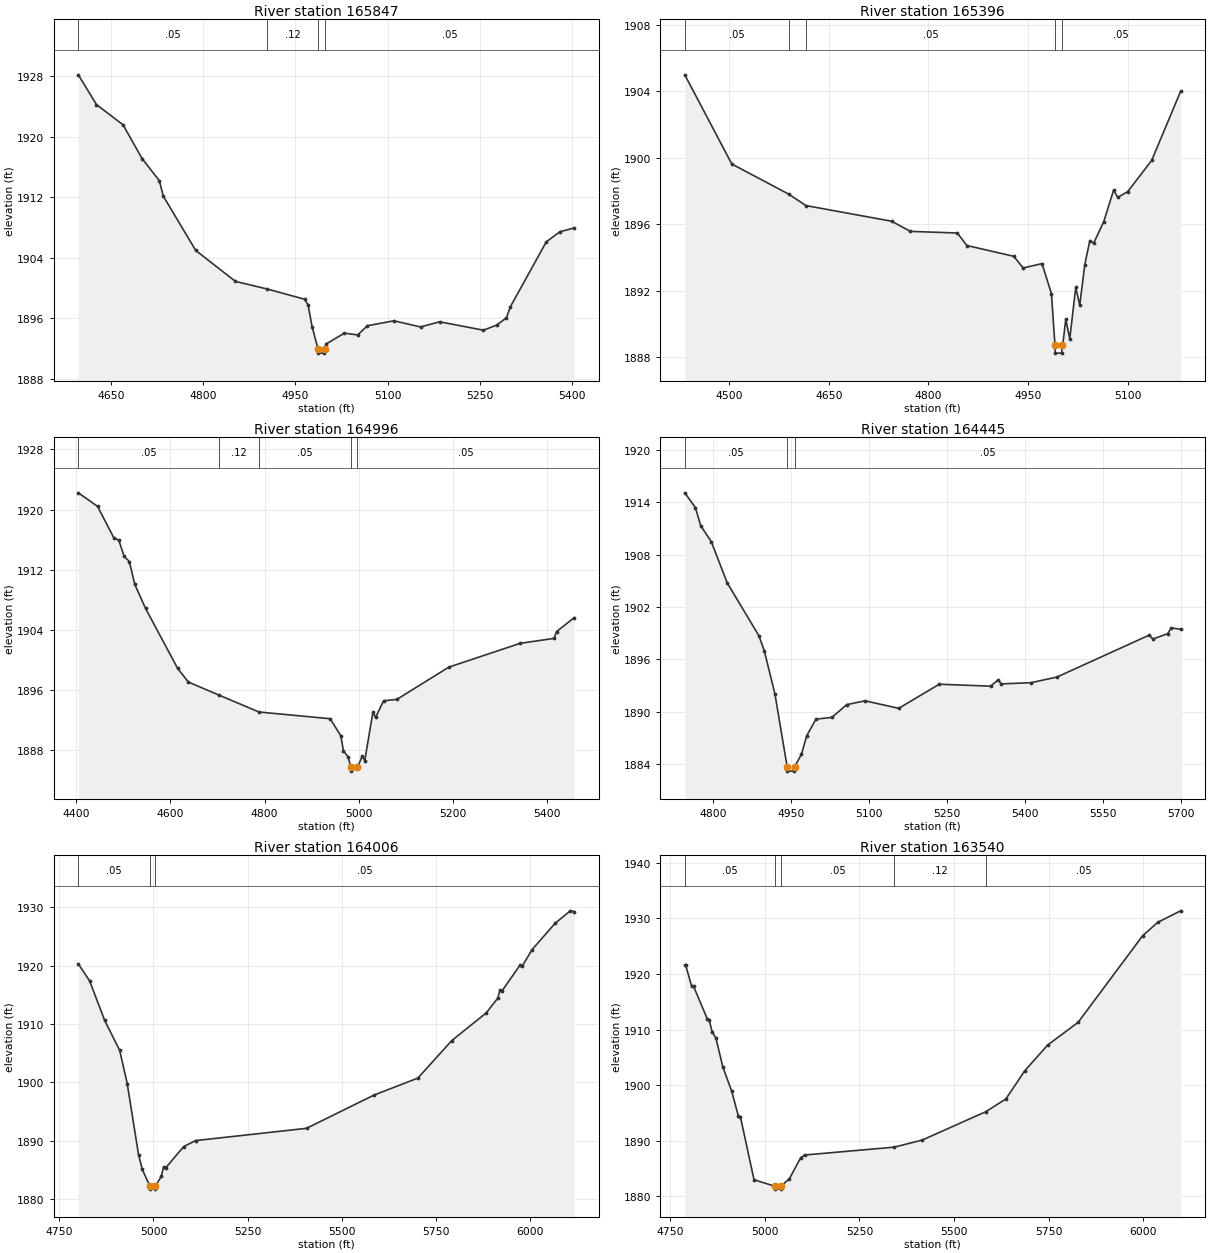
Type RM Length L Ch R = 1,165847,451,451,451
BEGIN DESCRIPTION:
Deadman Creek 216.0
END DESCRIPTION:
XS GIS Cut Line= 3
      1641855.01      6841888.00      1642205.00      6842088.00
      1642554.98      6842287.99
#Sta/Elev= 30
  4597.1 1928.17  4626.6 1924.24  4669.8 1921.57  4700.8 1917.10  4728.8 1914.19
  4735.3 1912.14  4787.9 1904.98  4852.6 1900.88  4903.8 1899.89  4964.9 1898.53
  4970.7 1897.76  4977.2 1894.90  4987.0 1891.91  4987.5 1891.41  4997.1 1891.41
  4997.6 1891.91  5000.2 1892.63  5029.7 1894.05  5051.3 1893.81  5067.2 1895.03
  5110.3 1895.68  5153.5 1894.87  5184.5 1895.55  5255.8 1894.44  5277.3 1895.11
  5293.2 1896.08  5299.7 1897.55  5358.0 1906.11  5380.3 1907.45  5403.3 1907.94
#Mann=4,-1,0
  4597.1    0.05       0  4903.8    0.12       0  4987.0    0.05       0
  4997.6    0.05       0
Bank Sta=4987,4997.6
Exp/Cntr=0.3,0.1

Type RM Length L Ch R = 1,165396,400,400,400
BEGIN DESCRIPTION:
Deadman Creek 215.0
END DESCRIPTION:
XS GIS Cut Line= 3
      1641954.99      6842087.99      1642355.00      6842488.00
      1642505.02      6842387.99
#Sta/Elev= 30
  4433.5 1904.99  4504.2 1899.63  4589.7 1897.82  4615.8 1897.13  4744.6 1896.19
  4772.9 1895.58  4843.6 1895.48  4857.8 1894.73  4928.5 1894.08  4942.6 1893.38
  4970.9 1893.64  4985.1 1891.84  4990.4 1888.76  4990.9 1888.26  5000.5 1888.26
  5001.0 1888.76  5002.2 1888.76  5006.7 1890.30  5012.7 1889.12  5021.7 1892.21
  5027.7 1891.14  5035.3 1893.58  5042.8 1895.01  5048.8 1894.88  5063.8 1896.16
  5078.8 1898.07  5084.8 1897.62  5099.9 1897.97  5135.9 1899.84  5179.5 1904.00
#Mann=5,-1,0
  4433.5    0.05       0  4589.7    0.12       0  4615.8    0.05       0
  4990.4    0.05       0  5001.0    0.05       0
Bank Sta=4990.4,5001
Exp/Cntr=0.3,0.1

Type RM Length L Ch R = 1,164996,551,551,551
BEGIN DESCRIPTION:
Deadman Creek 214.0
END DESCRIPTION:
XS GIS Cut Line= 3
      1641780.68      6842100.17      1642087.91      6842746.74
      1642192.06      6843066.97
#Sta/Elev= 30
  4404.4 1922.23  4445.1 1920.44  4479.5 1916.28  4490.5 1915.91  4501.6 1913.78
  4512.7 1913.09  4524.3 1910.05  4547.0 1906.88  4615.2 1898.89  4637.9 1897.08
  4704.0 1895.31  4788.0 1893.09  4938.8 1892.20  4961.6 1889.94  4967.1 1887.95
  4977.7 1887.06  4982.7 1885.73  4983.2 1885.23  4996.9 1885.73  5007.0 1887.21
  5012.5 1886.63  5029.7 1893.06  5035.3 1892.37  5052.5 1894.58  5080.7 1894.77
  5190.8 1899.05  5342.4 1902.22  5414.4 1902.88  5419.6 1903.77  5457.0 1905.64
#Mann=5,-1,0
  4404.4    0.05       0  4704.0    0.12       0  4788.0    0.05       0
  4982.7    0.05       0  4996.9    0.05       0
Bank Sta=4982.7,4996.9
Exp/Cntr=0.3,0.1

Type RM Length L Ch R = 1,164445,439,439,439
BEGIN DESCRIPTION:
Deadman Creek 213.0
END DESCRIPTION:
XS GIS Cut Line= 3
      1641504.99      6842387.97      1641555.00      6842638.00
      1642088.75      6843089.38
#Sta/Elev= 30
  4745.4 1915.08  4765.8 1913.39  4776.0 1911.31  4796.4 1909.48  4827.0 1904.76
  4888.2 1898.67  4898.4 1896.96  4918.8 1892.03  4942.3 1883.68  4942.8 1883.18
  4956.0 1883.18  4956.5 1883.68  4969.8 1885.09  4980.0 1887.24  4997.8 1889.14
  5028.4 1889.34  5057.0 1890.80  5092.1 1891.24  5157.0 1890.38  5235.0 1893.14
  5333.8 1892.92  5348.1 1893.63  5354.7 1893.18  5411.8 1893.32  5461.3 1893.96
  5639.3 1898.78  5645.9 1898.32  5674.4 1898.93  5681.4 1899.60  5699.4 1899.44
#Mann=3,-1,0
  4745.4    0.05       0  4942.3    0.03       0  4956.5    0.05       0
Bank Sta=4942.3,4956.5
Exp/Cntr=0.3,0.1

Type RM Length L Ch R = 1,164006,466,466,466
BEGIN DESCRIPTION:
Deadman Creek 212.0
END DESCRIPTION:
XS GIS Cut Line= 3
      1641254.96      6843038.00      1641455.00      6843038.00
      1642555.02      6843238.00
#Sta/Elev= 30
  4800.2 1920.31  4830.2 1917.40  4870.2 1910.62  4910.2 1905.46  4930.2 1899.77
  4960.2 1887.60  4970.2 1885.06  4990.5 1882.17  4991.0 1881.67  5004.4 1881.67
  5004.9 1882.17  5020.6 1883.84  5026.9 1885.47  5032.0 1885.29  5080.3 1888.97
  5112.0 1890.00  5406.8 1892.10  5585.9 1897.80  5702.8 1900.72  5793.0 1907.16
  5884.5 1911.90  5915.0 1914.41  5921.4 1915.85  5926.4 1915.66  5974.7 1920.14
  5979.8 1919.89  6006.5 1922.77  6067.5 1927.27  6108.1 1929.42  6118.3 1929.30
#Mann=3,-1,0
  4800.2    0.05       0  4990.5    0.05       0  5004.9    0.05       0
Bank Sta=4990.5,5004.9
Exp/Cntr=0.3,0.1

Type RM Length L Ch R = 1,163540,462,462,462
BEGIN DESCRIPTION:
Deadman Creek 211.0
END DESCRIPTION:
XS GIS Cut Line= 3
      1641304.99      6843538.00      1641505.00      6843488.00
      1642605.00      6843388.00
#Sta/Elev= 30
  4788.4 1921.53  4791.0 1921.53  4806.5 1917.79  4811.6 1917.78  4847.7 1911.94
  4852.8 1911.70  4860.6 1909.62  4870.9 1908.40  4888.9 1903.25  4912.1 1898.95
  4930.1 1894.40  4935.3 1894.31  4971.4 1882.95  5027.5 1881.76  5028.0 1881.26
  5041.4 1881.26  5041.9 1881.76  5064.9 1883.13  5095.0 1886.93  5105.0 1887.40
  5342.3 1888.82  5416.3 1890.10  5585.0 1895.23  5637.2 1897.50  5687.4 1902.59
  5747.7 1907.21  5828.0 1911.28  5998.7 1926.89  6038.9 1929.31  6099.1 1931.37
#Mann=5,-1,0
  4788.4    0.05       0  5027.5    0.05       0  5041.9    0.05       0
  5342.3    0.12       0  5585.0    0.05       0
Bank Sta=5027.5,5041.9
Exp/Cntr=0.3,0.1

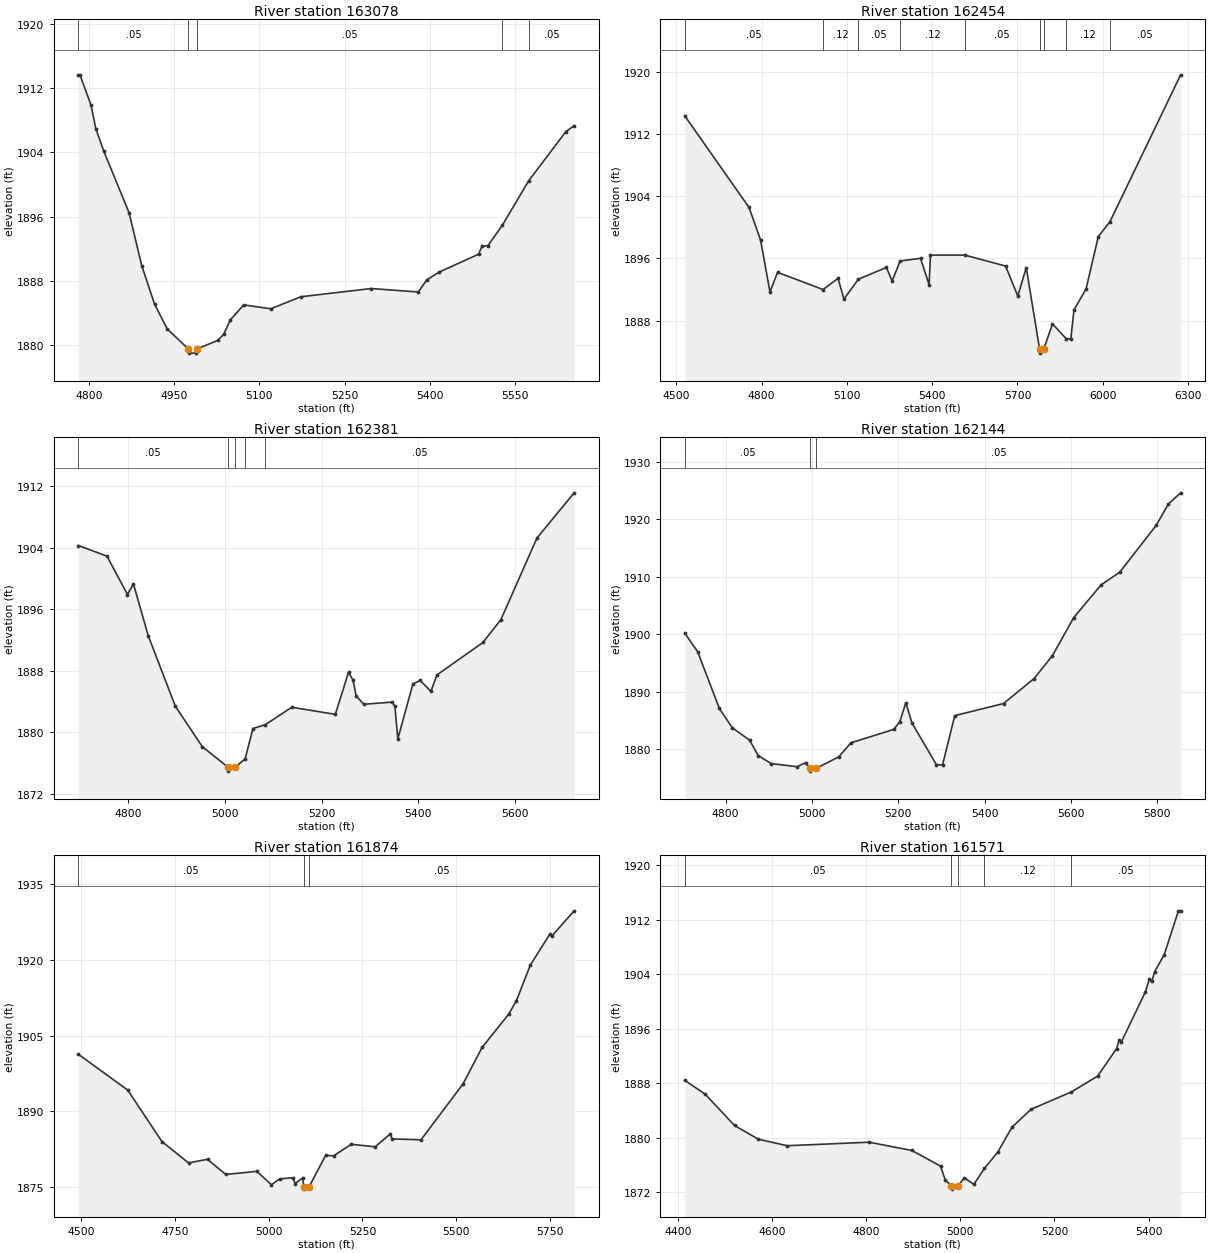
Type RM Length L Ch R = 1,163078,624,624,624
BEGIN DESCRIPTION:
Deadman Creek 210.0
END DESCRIPTION:
XS GIS Cut Line= 3
      1641505.00      6843988.00      1641705.00      6843888.00
      1642304.99      6843638.00
#Sta/Elev= 30
  4781.0 1913.62  4783.8 1913.62  4803.4 1909.85  4811.8 1906.93  4825.7 1904.16
  4870.4 1896.47  4892.8 1889.87  4915.2 1885.13  4937.5 1882.04  4975.0 1879.52
  4975.5 1879.02  4989.0 1879.02  4989.5 1879.52  5026.3 1880.59  5037.1 1881.34
  5048.5 1883.12  5072.3 1885.02  5120.0 1884.53  5173.1 1886.03  5297.1 1887.05
  5380.0 1886.62  5394.6 1888.11  5416.3 1889.08  5486.2 1891.32  5492.1 1892.29
  5502.9 1892.40  5528.0 1894.91  5574.3 1900.43  5640.0 1906.56  5654.6 1907.29
#Mann=5,-1,0
  4781.0    0.05       0  4975.0    0.05       0  4989.5    0.05       0
  5528.0    0.12       0  5574.3    0.05       0
Bank Sta=4975,4989.5
Exp/Cntr=0.3,0.1

Type RM Length L Ch R = 1,162454,73,73,73
BEGIN DESCRIPTION:
Mapping XS e244e1e5
END DESCRIPTION:
XS GIS Cut Line= 6
      1641552.35      6844473.78      1641964.66      6844417.36
      1642220.73      6844252.43      1642212.05      6844117.88
      1641995.04      6843892.19      1642524.56      6843683.85
#Sta/Elev= 30
  4529.7 1914.34  4755.7 1902.56  4796.3 1898.37  4829.4 1891.69  4856.1 1894.21
  5016.2 1892.00  5068.8 1893.44  5089.6 1890.77  5140.4 1893.33  5239.0 1894.84
  5259.1 1893.10  5287.3 1895.67  5359.0 1896.02  5389.2 1892.63  5394.0 1896.43
  5514.5 1896.43  5658.4 1895.02  5701.2 1891.17  5731.0 1894.82  5778.0 1884.32
  5778.5 1883.82  5792.5 1884.32  5823.2 1887.58  5870.9 1885.70  5887.7 1885.64
  5898.9 1889.39  5941.4 1892.07  5984.4 1898.81  6025.3 1900.72  6274.1 1919.62
#Mann=9,-1,0
  4529.7    0.05       0  5016.2    0.12       0  5140.4    0.05       0
  5287.3    0.12       0  5514.5    0.05       0  5778.0    0.05       0
  5792.5    0.05       0  5870.9    0.12       0  6025.3    0.05       0
Bank Sta=5778,5792.5
Exp/Cntr=0.3,0.1

Type RM Length L Ch R = 1,162381,237,237,237
BEGIN DESCRIPTION:
Mapping XS 83fb1f9c
END DESCRIPTION:
XS GIS Cut Line= 3
      1641769.35      6844560.59      1642068.82      6844452.08
      1642680.40      6844096.42
#Sta/Elev= 30
  4696.7 1904.26  4755.9 1902.88  4798.4 1897.90  4810.7 1899.28  4841.3 1892.56
  4897.3 1883.41  4953.2 1878.15  5006.6 1875.47  5007.1 1874.97  5021.1 1875.47
  5041.8 1876.55  5058.0 1880.50  5083.7 1881.00  5138.3 1883.26  5228.5 1882.34
  5255.8 1887.80  5265.3 1886.76  5271.5 1884.75  5287.3 1883.65  5346.0 1883.93
  5351.8 1883.37  5357.8 1879.16  5389.1 1886.30  5404.1 1886.74  5426.3 1885.33
  5438.8 1887.46  5533.9 1891.67  5571.1 1894.64  5645.6 1905.22  5722.7 1911.10
#Mann=5,-1,0
  4696.7    0.05       0  5006.6    0.05       0  5021.1    0.05       0
  5041.8    0.12       0  5083.7    0.05       0
Bank Sta=5006.6,5021.1
Exp/Cntr=0.3,0.1

Type RM Length L Ch R = 1,162144,270,270,270
BEGIN DESCRIPTION:
Deadman Creek 208.0
END DESCRIPTION:
XS GIS Cut Line= 3
      1641904.99      6844638.00      1642205.00      6844638.00
      1642804.98      6844038.02
#Sta/Elev= 30
  4705.7 1900.21  4735.7 1896.95  4785.7 1887.12  4815.7 1883.75  4855.7 1881.60
  4875.7 1878.91  4905.7 1877.53  4965.7 1876.98  4985.7 1877.69  4995.9 1876.71
  4996.4 1876.21  5010.5 1876.71  5062.3 1878.69  5090.6 1881.14  5189.6 1883.46
  5203.7 1884.82  5217.8 1888.09  5232.0 1884.56  5288.5 1877.34  5302.7 1877.28
  5331.0 1885.86  5444.1 1887.97  5514.8 1892.32  5557.2 1896.29  5606.7 1902.93
  5670.4 1908.64  5712.8 1910.78  5797.7 1918.97  5825.9 1922.67  5854.2 1924.62
#Mann=3,-1,0
  4705.7    0.05       0  4995.9    0.03       0  5010.5    0.05       0
Bank Sta=4995.9,5010.5
Exp/Cntr=0.3,0.1

Type RM Length L Ch R = 1,161874,303,303,303
BEGIN DESCRIPTION:
Deadman Creek 207.0
END DESCRIPTION:
XS GIS Cut Line= 3
      1641804.96      6844787.99      1642316.22      6844873.09
      1643106.15      6844721.18
#Sta/Elev= 30
  4492.1 1901.32  4623.9 1894.23  4715.2 1884.05  4786.1 1879.84  4836.8 1880.55
  4885.2 1877.55  4968.6 1878.17  5007.0 1875.51  5029.5 1876.68  5064.5 1876.90
  5070.3 1875.76  5090.6 1876.88  5093.5 1875.15  5094.0 1874.65  5108.1 1875.15
  5151.7 1881.31  5173.5 1881.25  5220.3 1883.52  5284.1 1883.02  5324.2 1885.57
  5329.3 1884.58  5406.3 1884.41  5518.3 1895.45  5569.2 1902.67  5640.5 1909.28
  5660.9 1911.94  5697.9 1918.95  5749.8 1925.06  5754.9 1924.66  5814.8 1929.68
#Mann=3,-1,0
  4492.1    0.05       0  5093.5    0.03       0  5108.1    0.05       0
Bank Sta=5093.5,5108.1
Exp/Cntr=0.3,0.1

Type RM Length L Ch R = 1,161571,330,330,330
BEGIN DESCRIPTION:
Mapping XS 0132a72b
END DESCRIPTION:
XS GIS Cut Line= 3
      1641883.03      6845079.87      1642216.35      6845157.99
      1642919.42      6845053.83
#Sta/Elev= 30
  4415.0 1888.43  4458.1 1886.42  4520.6 1881.81  4571.1 1879.80  4632.7 1878.84
  4806.5 1879.36  4897.5 1878.14  4958.2 1875.85  4968.3 1873.78  4981.1 1872.97
  4981.6 1872.47  4995.8 1872.97  5008.7 1874.14  5028.9 1873.16  5051.4 1875.52
  5079.5 1877.88  5109.8 1881.55  5150.2 1884.18  5235.9 1886.73  5291.8 1889.06
  5332.2 1893.10  5337.3 1894.32  5342.3 1894.09  5392.9 1901.37  5401.7 1903.25
  5406.8 1902.96  5413.1 1904.41  5433.3 1906.89  5463.4 1913.32  5468.1 1913.32
#Mann=5,-1,0
  4415.0    0.05       0  4981.1    0.05       0  4995.8    0.05       0
  5051.4    0.12       0  5235.9    0.05       0
Bank Sta=4981.1,4995.8
Exp/Cntr=0.3,0.1

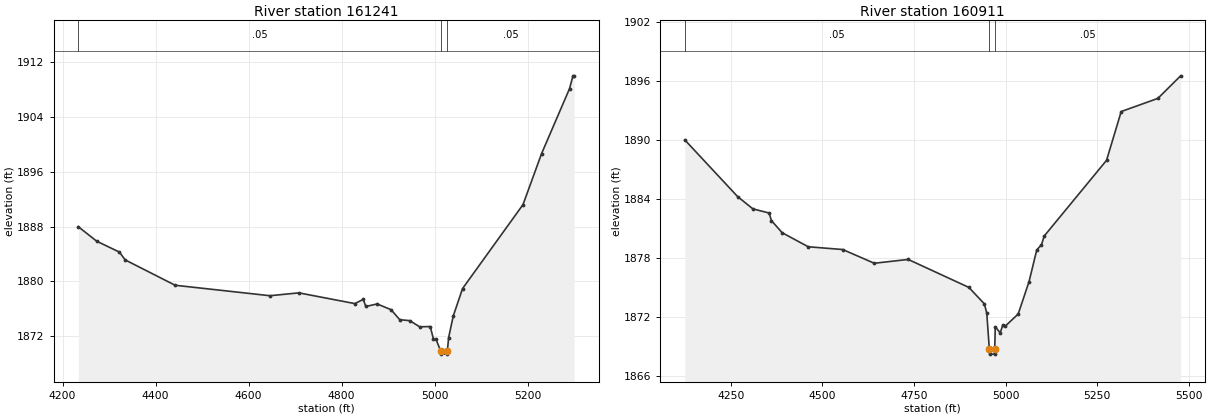
Type RM Length L Ch R = 1,161241,330,330,330
BEGIN DESCRIPTION:
Deadman Creek 206.0
END DESCRIPTION:
XS GIS Cut Line= 3
      1641791.06      6845159.55      1642505.00      6845438.00
      1642804.98      6845438.00
#Sta/Elev= 30
  4233.8 1887.98  4273.2 1885.87  4322.2 1884.27  4334.6 1883.13  4442.0 1879.43
  4645.9 1877.90  4708.0 1878.32  4828.4 1876.75  4846.6 1877.37  4852.0 1876.33
  4876.5 1876.70  4906.3 1875.86  4925.0 1874.40  4946.5 1874.26  4967.9 1873.36
  4990.6 1873.40  4997.4 1871.60  5002.6 1871.60  5012.8 1869.87  5013.3 1869.37
  5027.0 1869.37  5027.5 1869.87  5030.1 1871.77  5040.1 1874.94  5060.1 1878.95
  5190.1 1891.21  5230.1 1898.67  5290.1 1908.14  5297.6 1910.02  5300.1 1910.02
#Mann=3,-1,0
  4233.8    0.05       0  5012.8    0.05       0  5027.5    0.05       0
Bank Sta=5012.8,5027.5
Exp/Cntr=0.3,0.1

Type RM Length L Ch R = 1,160911,367,367,367
BEGIN DESCRIPTION:
Mapping XS 3471034c
END DESCRIPTION:
XS GIS Cut Line= 4
      1641665.15      6845207.27      1642220.73      6845606.60
      1642455.11      6845771.53      1642837.09      6845767.19
#Sta/Elev= 30
  4124.5 1890.01  4268.7 1884.23  4310.4 1882.98  4354.6 1882.56  4360.8 1881.79
  4390.2 1880.55  4461.4 1879.12  4555.3 1878.84  4641.5 1877.44  4734.0 1877.83
  4899.5 1874.98  4941.9 1873.30  4948.4 1872.35  4955.4 1868.68  4955.9 1868.18
  4969.7 1868.18  4970.2 1868.68  4971.5 1870.97  4985.1 1870.35  4992.4 1871.17
  4998.5 1871.02  5034.2 1872.27  5063.8 1875.58  5084.8 1878.80  5097.7 1879.33
  5105.2 1880.22  5275.2 1887.93  5315.2 1892.90  5415.2 1894.24  5477.3 1896.54
#Mann=3,-1,0
  4124.5    0.05       0  4955.4    0.05       0  4970.2    0.05       0
Bank Sta=4955.4,4970.2
Exp/Cntr=0.3,0.1