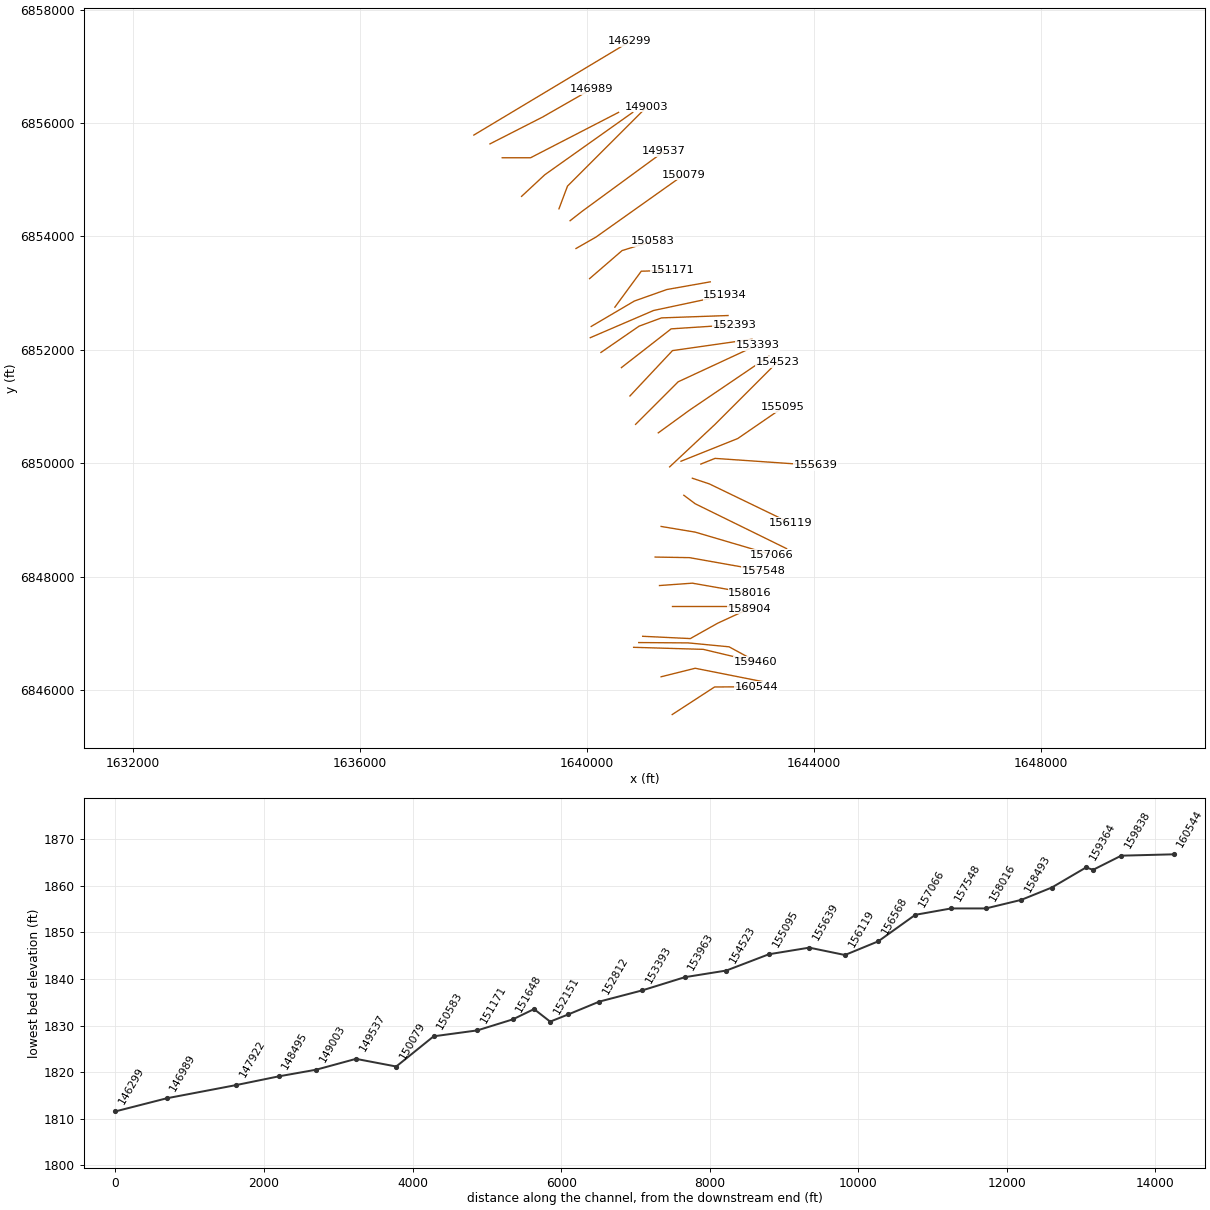
HEC-RAS study Deadman Creek.prj: Deadman Creek Base Level Engineering

--- Deadman Creek.g01 (geometry) --- (continued)

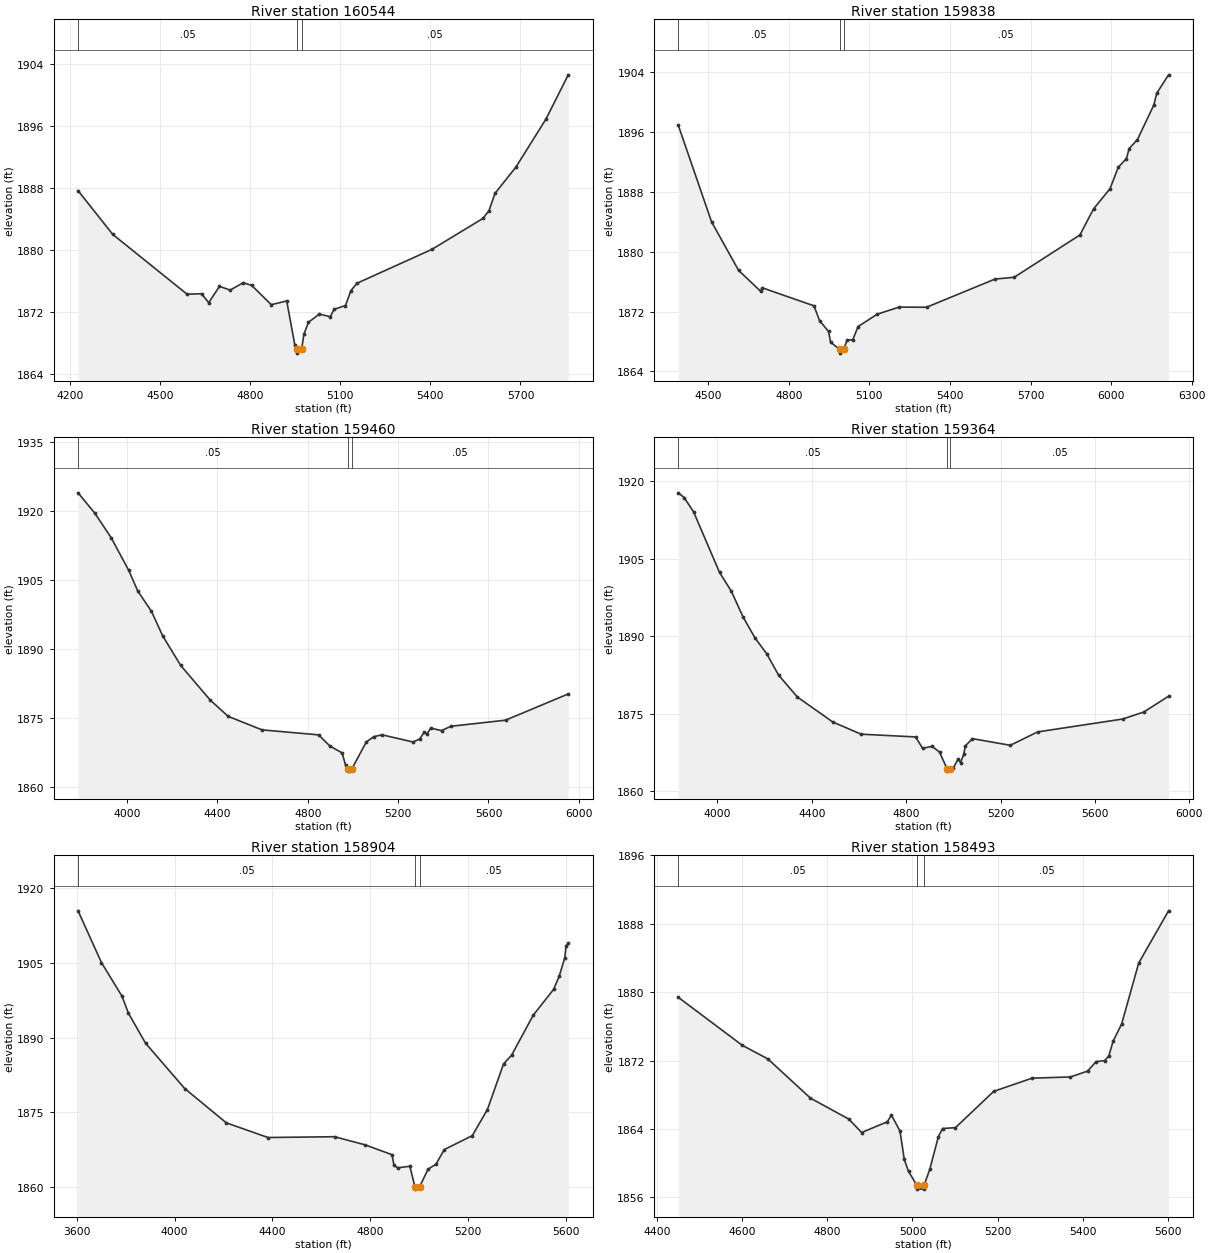
Type RM Length L Ch R = 1,160544,706,706,706
BEGIN DESCRIPTION:
Mapping XS bbfb9208
END DESCRIPTION:
XS GIS Cut Line= 3
      1641500.23      6845571.87      1642246.78      6846057.99
      1642989.00      6846062.33
#Sta/Elev= 30
  4226.1 1887.69  4341.6 1882.05  4589.3 1874.33  4637.5 1874.39  4661.4 1873.24
  4697.2 1875.34  4733.0 1874.86  4776.4 1875.82  4804.6 1875.46  4869.9 1872.98
  4921.3 1873.46  4948.3 1867.78  4956.0 1867.23  4956.5 1866.73  4970.8 1867.23
  4978.6 1869.18  4993.7 1870.71  5029.9 1871.77  5066.2 1871.43  5079.0 1872.38
  5117.0 1872.87  5135.2 1874.79  5155.2 1875.74  5405.2 1880.12  5575.2 1884.11
  5595.2 1885.12  5615.2 1887.34  5685.2 1890.75  5785.2 1896.94  5859.2 1902.63
#Mann=3,-1,0
  4226.1    0.05       0  4956.0    0.03       0  4970.8    0.05       0
Bank Sta=4956,4970.8
Exp/Cntr=0.3,0.1

Type RM Length L Ch R = 1,159838,378,378,378
BEGIN DESCRIPTION:
Deadman Creek 205.0
END DESCRIPTION:
XS GIS Cut Line= 3
      1641305.01      6846238.00      1641905.00      6846388.00
      1643088.74      6846153.48
#Sta/Elev= 30
  4388.7 1896.91  4512.4 1884.01  4612.9 1877.52  4695.3 1874.71  4700.5 1875.19
  4893.8 1872.77  4914.4 1870.80  4947.9 1869.34  4955.6 1867.90  4989.4 1866.94
  4989.9 1866.44  5004.3 1866.94  5017.3 1868.20  5037.9 1868.21  5058.1 1870.00
  5129.5 1871.65  5211.0 1872.60  5313.0 1872.58  5567.8 1876.35  5639.2 1876.59
  5883.9 1882.25  5934.8 1885.75  5996.0 1888.44  6026.6 1891.31  6057.0 1892.47
  6067.4 1893.82  6097.9 1895.01  6159.1 1899.63  6169.7 1901.20  6213.9 1903.68
#Mann=3,-1,0
  4388.7    0.05       0  4989.4    0.05       0  5004.3    0.05       0
Bank Sta=4989.4,5004.3
Exp/Cntr=0.3,0.1

Type RM Length L Ch R = 1,159460,96,96,96
BEGIN DESCRIPTION:
Deadman Creek 204.0
END DESCRIPTION:
XS GIS Cut Line= 3
      1640820.45      6846757.18      1642046.91      6846721.29
      1642965.12      6846502.95
#Sta/Elev= 30
  3782.6 1923.94  3857.2 1919.49  3928.9 1914.21  4007.2 1907.06  4047.3 1902.56
  4107.3 1898.20  4157.3 1892.84  4237.3 1886.39  4367.4 1878.89  4447.4 1875.32
  4597.5 1872.38  4847.6 1871.30  4897.6 1868.88  4951.8 1867.38  4967.7 1864.65
  4980.2 1863.91  4980.7 1863.41  4995.1 1863.91  5059.0 1869.74  5091.8 1870.90
  5128.8 1871.31  5265.6 1869.75  5295.4 1870.39  5316.0 1871.89  5326.3 1871.48
  5344.8 1872.76  5392.2 1872.23  5434.3 1873.17  5675.7 1874.49  5953.4 1880.20
#Mann=3,-1,0
  3782.6    0.05       0  4980.2    0.05       0  4995.1    0.05       0
Bank Sta=4980.2,4995.1
Exp/Cntr=0.3,0.1

Type RM Length L Ch R = 1,159364,460,460,460
BEGIN DESCRIPTION:
Mapping XS 2f5ce723
END DESCRIPTION:
XS GIS Cut Line= 4
      1640910.27      6846840.94      1641783.68      6846834.96
      1642501.59      6846766.16      1642926.33      6846535.84
#Sta/Elev= 30
  3834.3 1917.78  3859.0 1916.87  3899.0 1914.10  4009.0 1902.36  4059.0 1898.73
  4109.0 1893.72  4159.0 1889.71  4209.0 1886.62  4259.0 1882.51  4339.0 1878.25
  4489.0 1873.42  4609.0 1871.06  4839.7 1870.53  4869.8 1868.33  4910.0 1868.71
  4941.5 1867.59  4972.8 1864.41  4973.3 1863.91  4987.7 1864.41  5000.4 1864.58
  5020.5 1866.25  5030.5 1865.58  5044.2 1867.16  5050.6 1868.78  5080.8 1870.20
  5241.5 1868.91  5357.1 1871.50  5717.2 1873.99  5807.8 1875.36  5912.1 1878.41
#Mann=3,-1,0
  3834.3    0.05       0  4972.8    0.05       0  4987.7    0.05       0
Bank Sta=4972.8,4987.7
Exp/Cntr=0.3,0.1

Type RM Length L Ch R = 1,158904,411,411,411
BEGIN DESCRIPTION:
Deadman Creek 203.0
END DESCRIPTION:
XS GIS Cut Line= 4
      1640979.51      6846951.61      1641819.30      6846911.20
      1642301.17      6847181.95      1642854.96      6847437.98
#Sta/Elev= 30
  3605.3 1915.47  3700.9 1905.09  3785.3 1898.30  3811.0 1894.94  3881.1 1888.91
  4041.3 1879.80  4211.5 1872.91  4381.7 1869.97  4653.6 1870.13  4777.9 1868.51
  4888.5 1866.52  4896.5 1864.42  4911.4 1863.89  4961.6 1864.20  4981.9 1860.11
  4982.4 1859.61  5001.5 1860.11  5036.1 1863.62  5068.2 1864.61  5102.2 1867.55
  5216.8 1870.35  5278.4 1875.58  5344.5 1884.75  5377.3 1886.49  5465.7 1894.52
  5548.9 1899.70  5571.8 1902.32  5594.7 1906.06  5600.2 1908.44  5608.9 1908.97
#Mann=3,-1,0
  3605.3    0.05       0  4981.9    0.05       0  5001.5    0.05       0
Bank Sta=4981.9,5001.5
Exp/Cntr=0.3,0.1

Type RM Length L Ch R = 1,158493,477,477,477
BEGIN DESCRIPTION:
Deadman Creek 202.0
END DESCRIPTION:
XS GIS Cut Line= 3
      1641505.02      6847488.00      1642055.00      6847488.00
      1642655.02      6847488.00
#Sta/Elev= 30
  4450.7 1879.39  4600.7 1873.78  4660.7 1872.19  4760.7 1867.60  4850.7 1865.15
  4880.7 1863.58  4940.7 1864.83  4950.7 1865.61  4970.7 1863.75  4980.7 1860.45
  4990.7 1859.03  5009.7 1857.46  5010.2 1856.96  5027.0 1856.96  5027.5 1857.46
  5040.7 1859.29  5060.7 1863.10  5070.7 1864.05  5100.7 1864.15  5190.7 1868.40
  5280.7 1869.94  5370.7 1870.08  5410.7 1870.76  5430.7 1871.87  5450.7 1871.99
  5460.7 1872.56  5470.7 1874.27  5490.7 1876.27  5530.7 1883.40  5600.7 1889.51
#Mann=3,-1,0
  4450.7    0.05       0  5009.7    0.05       0  5027.5    0.05       0
Bank Sta=5009.7,5027.5
Exp/Cntr=0.3,0.1

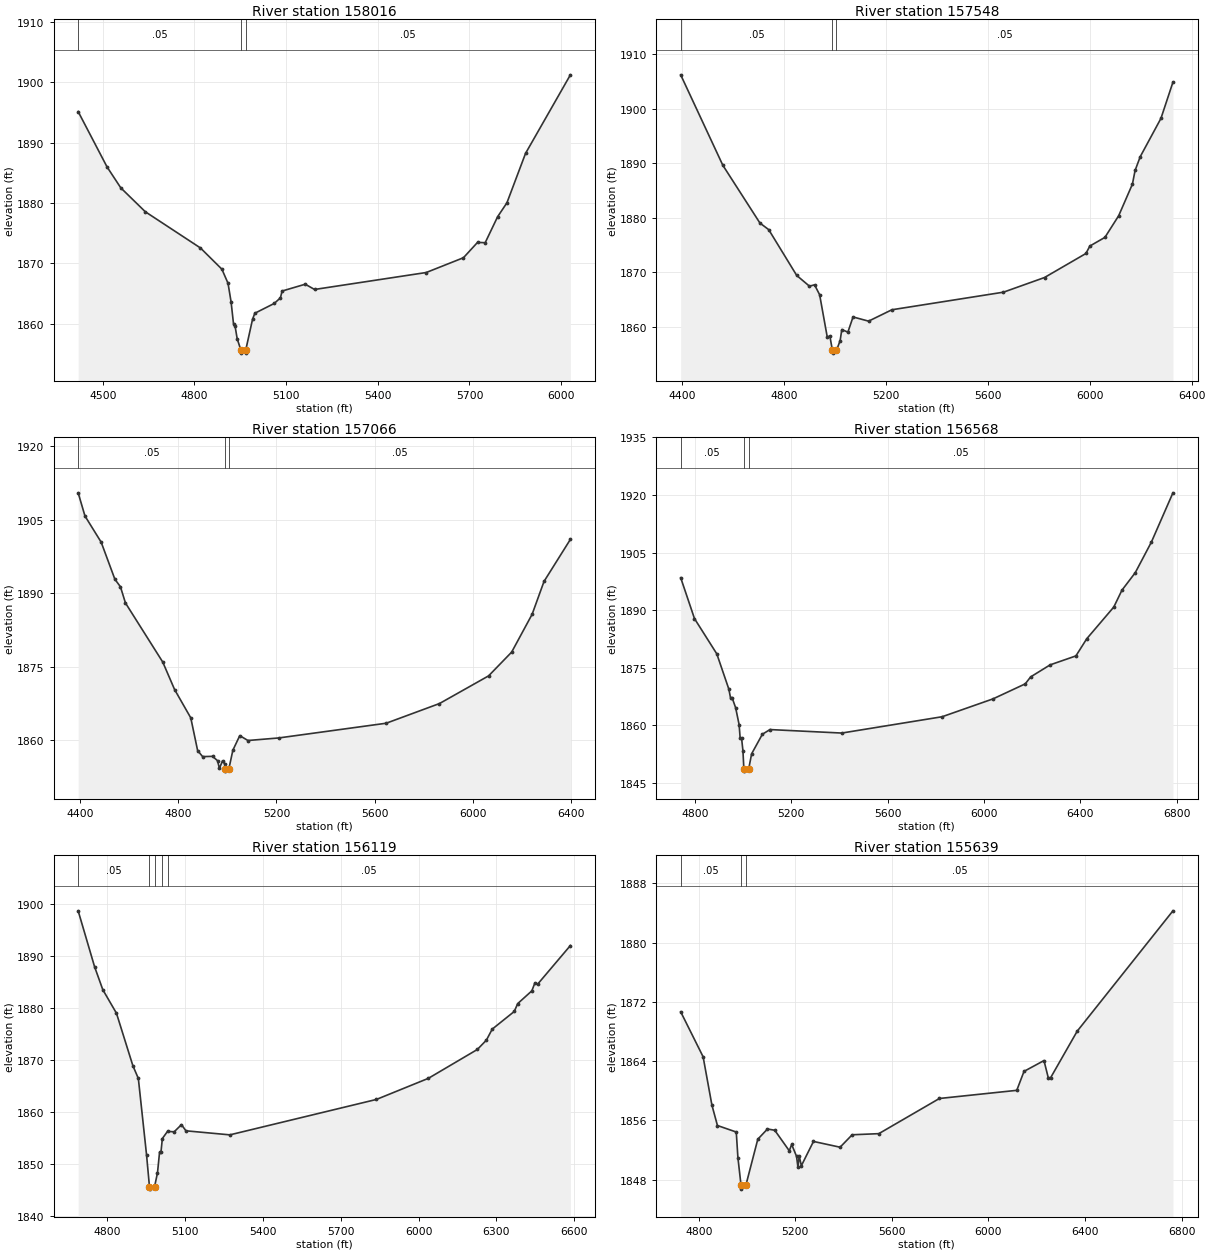
Type RM Length L Ch R = 1,158016,468,468,468
BEGIN DESCRIPTION:
Deadman Creek 201.0
END DESCRIPTION:
XS GIS Cut Line= 3
      1641275.90      6847846.19      1641855.00      6847888.00
      1642869.63      6847710.76
#Sta/Elev= 30
  4419.7 1895.15  4514.2 1885.98  4559.2 1882.51  4639.4 1878.55  4819.8 1872.55
  4890.0 1869.03  4910.1 1866.69  4920.1 1863.61  4928.0 1859.98  4933.0 1859.62
  4940.1 1857.49  4952.2 1855.62  4952.6 1855.12  4967.6 1855.12  4968.0 1855.62
  4990.3 1860.73  4997.8 1861.73  5061.2 1863.35  5081.5 1864.28  5087.0 1865.41
  5162.7 1866.54  5193.2 1865.67  5558.6 1868.48  5680.4 1870.93  5726.4 1873.47
  5751.5 1873.42  5792.1 1877.72  5822.6 1880.03  5883.5 1888.22  6030.3 1901.24
#Mann=3,-1,0
  4419.7    0.05       0  4952.2    0.05       0  4968.0    0.05       0
Bank Sta=4952.2,4968
Exp/Cntr=0.3,0.1

Type RM Length L Ch R = 1,157548,482,482,482
BEGIN DESCRIPTION:
Deadman Creek 200.0
END DESCRIPTION:
XS GIS Cut Line= 3
      1641199.54      6848348.31      1641805.00      6848338.00
      1643111.32      6848106.04
#Sta/Elev= 30
  4394.2 1906.21  4559.7 1889.60  4705.3 1879.00  4739.7 1877.79  4849.7 1869.38
  4899.7 1867.41  4919.7 1867.66  4939.7 1865.83  4969.7 1858.03  4979.7 1858.29
  4989.8 1855.62  4990.2 1855.12  5005.7 1855.62  5020.1 1857.41  5026.7 1859.45
  5050.5 1858.97  5070.8 1861.76  5131.8 1860.99  5223.2 1863.08  5661.3 1866.31
  5822.4 1869.00  5984.9 1873.41  6000.4 1874.78  6059.5 1876.37  6113.5 1880.34
  6167.5 1886.15  6177.9 1888.65  6198.2 1891.19  6279.5 1898.22  6326.5 1904.86
#Mann=3,-1,0
  4394.2    0.05       0  4989.8    0.05       0  5005.7    0.05       0
Bank Sta=4989.8,5005.7
Exp/Cntr=0.3,0.1

Type RM Length L Ch R = 1,157066,498,498,498
BEGIN DESCRIPTION:
Deadman Creek 199.0
END DESCRIPTION:
XS GIS Cut Line= 3
      1641305.04      6848887.99      1641905.00      6848788.00
      1643244.56      6848393.07
#Sta/Elev= 30
  4392.3 1910.46  4420.1 1905.73  4486.0 1900.41  4541.8 1892.86  4564.6 1891.31
  4584.9 1888.02  4736.9 1875.97  4785.1 1870.37  4851.0 1864.60  4878.9 1857.94
  4899.2 1856.71  4939.7 1856.76  4960.0 1855.88  4967.6 1854.30  4980.3 1855.86
  4990.4 1855.14  4990.5 1854.25  4990.9 1853.75  5006.3 1854.25  5022.4 1858.01
  5050.5 1860.98  5083.8 1859.99  5209.0 1860.51  5646.9 1863.51  5863.8 1867.52
  6063.9 1873.16  6157.8 1878.00  6241.2 1885.71  6289.7 1892.41  6397.1 1900.98
#Mann=3,-1,0
  4392.3    0.05       0  4990.5    0.05       0  5006.3    0.05       0
Bank Sta=4990.5,5006.3
Exp/Cntr=0.3,0.1

Type RM Length L Ch R = 1,156568,449,449,449
BEGIN DESCRIPTION:
Deadman Creek 198.0
END DESCRIPTION:
XS GIS Cut Line= 3
      1641704.97      6849438.02      1641905.00      6849288.00
      1643515.40      6848497.24
#Sta/Elev= 30
  4740.9 1898.47  4798.2 1887.81  4890.9 1878.62  4940.9 1869.43  4948.2 1867.06
  4954.5 1867.18  4969.1 1864.58  4983.6 1860.16  4987.8 1856.68  4993.7 1856.68
  4999.4 1853.40  5003.3 1848.57  5003.8 1848.07  5023.1 1848.57  5035.5 1852.59
  5080.1 1857.68  5111.8 1858.90  5409.7 1857.99  5826.5 1862.24  6038.1 1866.90
  6171.8 1870.81  6194.1 1872.62  6275.2 1875.76  6382.1 1878.09  6427.1 1882.56
  6539.5 1890.83  6573.1 1895.20  6628.6 1899.78  6695.4 1907.73  6785.0 1920.58
#Mann=3,-1,0
  4740.9    0.05       0  5003.3    0.05       0  5023.1    0.05       0
Bank Sta=5003.3,5023.1
Exp/Cntr=0.3,0.1

Type RM Length L Ch R = 1,156119,480,480,480
BEGIN DESCRIPTION:
Deadman Creek 197.0
END DESCRIPTION:
XS GIS Cut Line= 3
      1641854.97      6849738.01      1642155.00      6849638.00
      1643577.90      6848950.37
#Sta/Elev= 30
  4688.6 1898.72  4751.9 1887.95  4783.5 1883.54  4836.2 1879.00  4899.4 1868.90
  4920.5 1866.44  4952.2 1851.69  4963.3 1845.63  4963.8 1845.13  4983.1 1845.63
  4994.3 1848.27  5002.2 1852.21  5007.6 1852.21  5013.0 1854.87  5032.9 1856.25
  5058.6 1856.17  5086.7 1857.55  5103.8 1856.36  5273.1 1855.58  5837.8 1862.40
  6037.8 1866.46  6226.6 1872.02  6261.4 1873.81  6284.0 1875.94  6368.9 1879.34
  6382.1 1880.85  6436.6 1883.31  6448.7 1884.87  6459.2 1884.61  6585.2 1892.04
#Mann=5,-1,0
  4688.6    0.05       0  4963.3    0.05       0  4983.1    0.05       0
  5013.0    0.12       0  5032.9    0.05       0
Bank Sta=4963.3,4983.1
Exp/Cntr=0.3,0.1

Type RM Length L Ch R = 1,155639,544,544,544
BEGIN DESCRIPTION:
Deadman Creek 196.0
END DESCRIPTION:
XS GIS Cut Line= 3
      1642004.97      6849987.99      1642255.00      6850088.00
      1644020.30      6849966.00
#Sta/Elev= 30
  4725.4 1870.66  4818.3 1864.58  4854.7 1858.06  4877.6 1855.30  4955.6 1854.42
  4962.4 1850.97  4975.4 1847.21  4975.9 1846.71  4995.2 1847.21  5044.8 1853.45
  5084.9 1854.83  5115.0 1854.66  5175.1 1851.89  5185.1 1852.74  5205.2 1851.14
  5211.2 1849.64  5216.2 1851.20  5225.2 1849.87  5275.4 1853.15  5385.6 1852.37
  5435.7 1854.05  5546.0 1854.20  5797.0 1858.95  6117.4 1860.05  6147.4 1862.61
  6230.1 1864.07  6247.7 1861.77  6257.7 1861.76  6367.7 1868.04  6764.2 1884.29
#Mann=3,-1,0
  4725.4    0.05       0  4975.4    0.05       0  4995.2    0.05       0
Bank Sta=4975.4,4995.2
Exp/Cntr=0.3,0.1

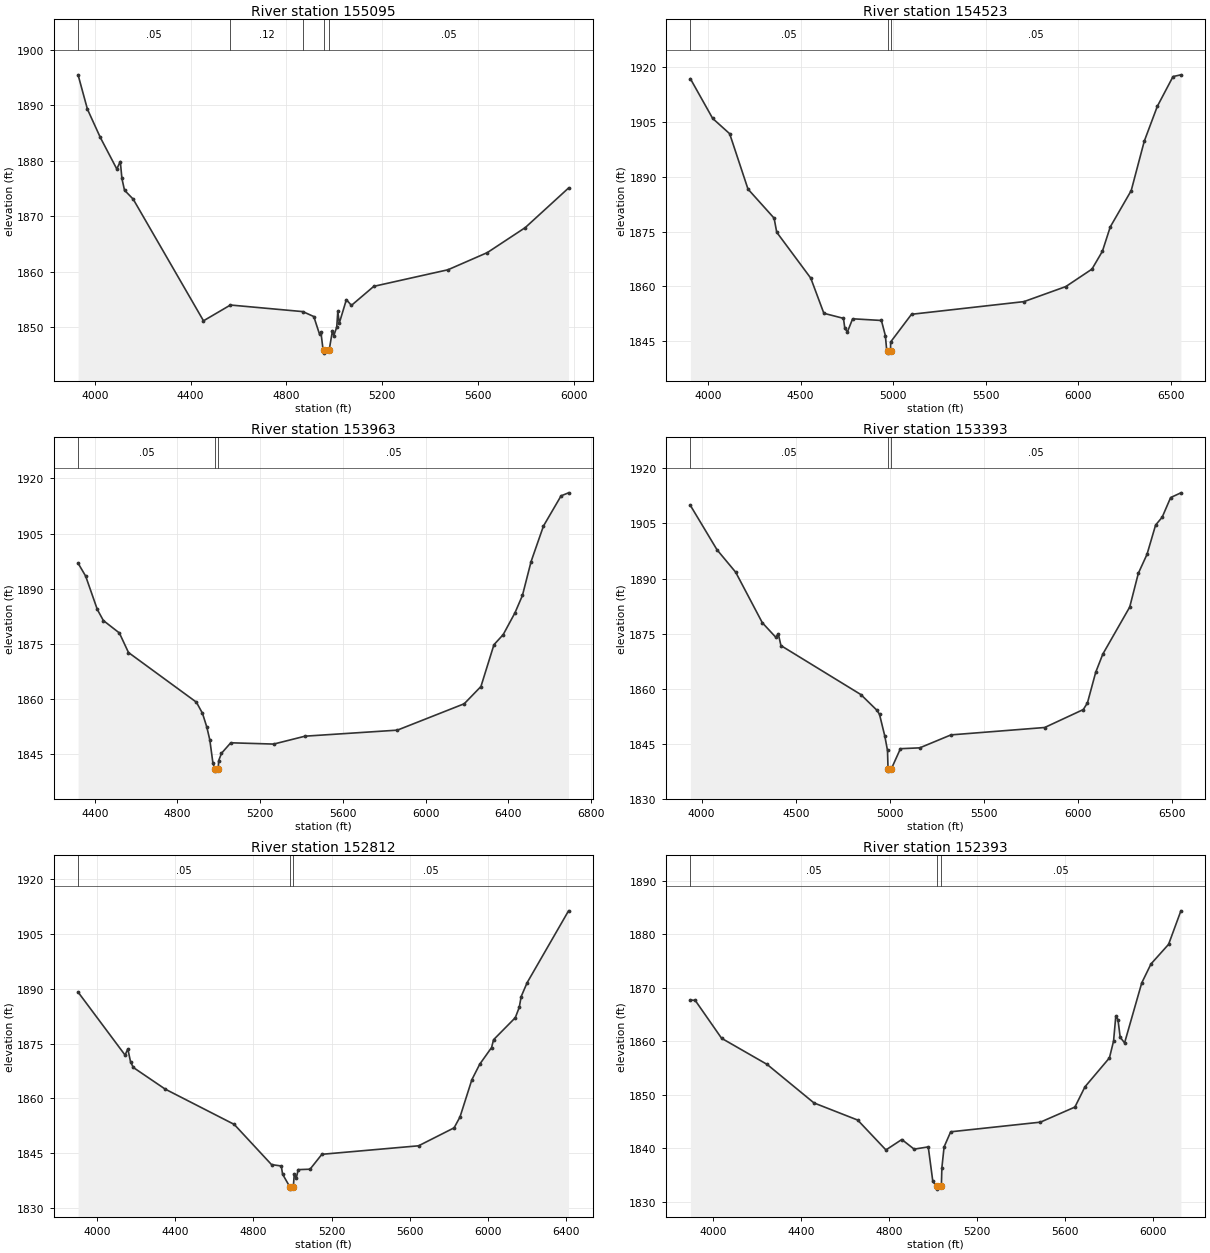
Type RM Length L Ch R = 1,155095,572,572,572
BEGIN DESCRIPTION:
Deadman Creek 195.0
END DESCRIPTION:
XS GIS Cut Line= 3
      1641654.99      6850037.99      1642655.00      6850438.00
      1643455.02      6850988.02
#Sta/Elev= 30
  3930.4 1895.50  3969.5 1889.30  4023.3 1884.20  4092.0 1878.52  4106.8 1879.86
  4113.5 1876.80  4124.3 1874.68  4160.6 1873.07  4454.1 1851.12  4566.6 1853.97
  4869.0 1852.78  4914.6 1851.89  4938.8 1848.67  4944.2 1849.13  4953.6 1845.80
  4958.2 1845.79  4958.7 1845.29  4978.6 1845.79  4992.6 1849.34  4998.0 1848.43
  5010.5 1849.99  5014.9 1852.84  5021.0 1850.69  5050.7 1854.94  5071.7 1853.90
  5165.2 1857.34  5474.9 1860.33  5639.3 1863.43  5797.6 1867.94  5978.3 1875.08
#Mann=5,-1,0
  3930.4    0.05       0  4566.6    0.12       0  4869.0    0.05       0
  4958.2    0.05       0  4978.6    0.05       0
Bank Sta=4958.2,4978.6
Exp/Cntr=0.3,0.1

Type RM Length L Ch R = 1,154523,560,560,560
BEGIN DESCRIPTION:
Deadman Creek 194.0
END DESCRIPTION:
XS GIS Cut Line= 3
      1641454.97      6849937.97      1642255.00      6850688.00
      1643355.03      6851788.03
#Sta/Elev= 30
  3903.8 1916.75  4024.2 1905.91  4116.1 1901.73  4215.2 1886.61  4356.4 1878.67
  4370.6 1874.82  4554.7 1862.28  4625.5 1852.68  4731.5 1851.30  4738.8 1848.56
  4753.0 1847.62  4781.1 1851.18  4936.7 1850.72  4958.2 1846.55  4965.0 1842.72
  4969.7 1842.30  4970.1 1841.80  4986.1 1842.30  4986.5 1844.84  5099.4 1852.41
  5707.5 1855.87  5933.8 1859.98  6075.2 1864.75  6131.8 1869.64  6174.2 1876.28
  6287.4 1886.19  6358.1 1899.70  6428.8 1909.23  6513.6 1917.35  6556.1 1917.82
#Mann=3,-1,0
  3903.8    0.05       0  4969.7    0.05       0  4986.1    0.05       0
Bank Sta=4969.7,4986.1
Exp/Cntr=0.3,0.1

Type RM Length L Ch R = 1,153963,570,570,570
BEGIN DESCRIPTION:
Deadman Creek 193.0
END DESCRIPTION:
XS GIS Cut Line= 3
      1641255.04      6850538.03      1641805.00      6850938.00
      1643204.98      6851887.99
#Sta/Elev= 30
  4319.2 1896.95  4355.9 1893.43  4412.3 1884.35  4441.6 1881.34  4518.9 1877.96
  4563.0 1872.64  4891.4 1859.13  4920.8 1856.11  4941.7 1852.37  4956.3 1848.87
  4971.0 1842.70  4980.4 1840.87  4980.8 1840.37  4996.8 1840.87  4999.2 1843.21
  5012.7 1845.22  5057.6 1848.08  5265.1 1847.73  5417.0 1849.88  5863.1 1851.52
  6186.6 1858.70  6267.4 1863.39  6330.3 1874.76  6375.2 1877.53  6432.1 1883.46
  6468.0 1888.16  6510.0 1897.40  6569.8 1907.06  6654.9 1915.27  6691.1 1916.09
#Mann=3,-1,0
  4319.2    0.05       0  4980.4    0.05       0  4996.8    0.05       0
Bank Sta=4980.4,4996.8
Exp/Cntr=0.3,0.1

Type RM Length L Ch R = 1,153393,581,581,581
BEGIN DESCRIPTION:
Deadman Creek 192.0
END DESCRIPTION:
XS GIS Cut Line= 3
      1640855.03      6850688.03      1641605.00      6851438.00
      1643005.04      6852088.02
#Sta/Elev= 30
  3940.4 1909.91  4081.8 1897.83  4180.8 1891.73  4322.2 1877.97  4392.9 1874.05
  4407.0 1874.91  4421.2 1871.74  4845.5 1858.40  4930.3 1854.15  4944.4 1853.02
  4972.7 1847.06  4986.9 1843.17  4989.8 1838.05  4990.2 1837.55  5006.2 1838.05
  5055.5 1843.66  5158.1 1843.89  5323.9 1847.42  5821.3 1849.43  6026.4 1854.32
  6048.4 1856.13  6092.5 1864.50  6130.0 1869.42  6272.9 1882.24  6318.7 1891.44
  6364.5 1896.57  6410.3 1904.57  6445.3 1906.72  6490.1 1912.06  6544.6 1913.35
#Mann=3,-1,0
  3940.4    0.05       0  4989.8    0.05       0  5006.2    0.05       0
Bank Sta=4989.8,5006.2
Exp/Cntr=0.3,0.1

Type RM Length L Ch R = 1,152812,419,419,419
BEGIN DESCRIPTION:
Deadman Creek 191.0
END DESCRIPTION:
XS GIS Cut Line= 3
      1640755.00      6851188.00      1641505.00      6851988.00
      1642905.01      6852188.00
#Sta/Elev= 30
  3902.6 1889.11  4143.2 1871.85  4157.3 1873.53  4171.5 1869.96  4185.6 1868.45
  4348.3 1862.54  4702.0 1852.86  4892.9 1841.85  4942.8 1841.47  4949.6 1839.22
  4987.9 1835.63  4988.3 1835.13  5004.4 1835.63  5009.3 1839.24  5019.4 1838.11
  5029.5 1840.47  5090.1 1840.59  5150.7 1844.67  5645.7 1847.00  5827.5 1851.92
  5857.8 1854.91  5918.4 1865.10  5958.8 1869.36  6019.4 1873.92  6029.5 1876.06
  6140.7 1882.09  6160.9 1884.90  6171.0 1887.90  6201.3 1891.68  6413.4 1911.37
#Mann=3,-1,0
  3902.6    0.05       0  4987.9    0.05       0  5004.4    0.05       0
Bank Sta=4987.9,5004.4
Exp/Cntr=0.3,0.1

Type RM Length L Ch R = 1,152393,242,242,242
BEGIN DESCRIPTION:
Deadman Creek 190.0
END DESCRIPTION:
XS GIS Cut Line= 3
      1640605.03      6851688.02      1641481.97      6852371.53
      1642600.85      6852444.39
#Sta/Elev= 30
  3895.1 1867.69  3916.8 1867.64  4037.1 1860.55  4244.3 1855.67  4457.8 1848.47
  4656.8 1845.27  4785.3 1839.69  4857.6 1841.64  4913.7 1839.84  4978.0 1840.26
  4998.8 1833.80  5016.9 1832.87  5017.4 1832.37  5037.6 1832.87  5040.0 1836.36
  5050.1 1840.26  5080.1 1843.08  5488.6 1844.88  5645.7 1847.70  5691.4 1851.48
  5802.9 1856.89  5821.7 1860.04  5831.7 1864.63  5841.7 1864.04  5851.8 1860.75
  5871.8 1859.69  5950.0 1870.90  5992.1 1874.44  6072.2 1878.10  6128.2 1884.36
#Mann=3,-1,0
  3895.1    0.05       0  5016.9    0.05       0  5037.6    0.05       0
Bank Sta=5016.9,5037.6
Exp/Cntr=0.3,0.1

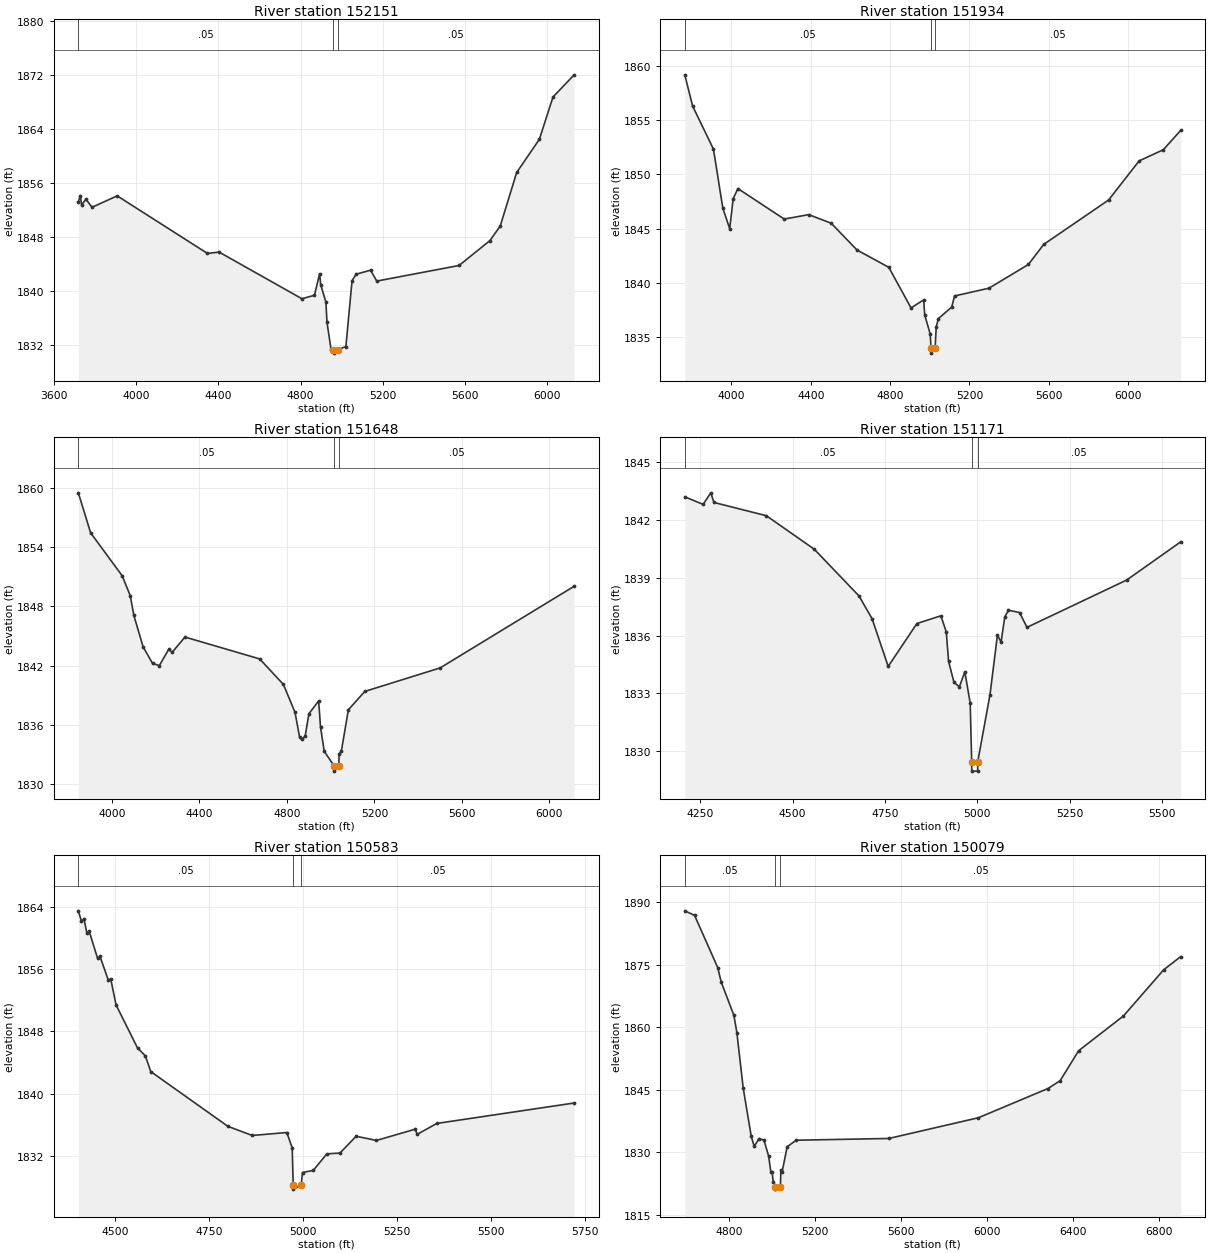
Type RM Length L Ch R = 1,152151,217,217,217
BEGIN DESCRIPTION:
Mapping XS de6c9c38
END DESCRIPTION:
XS GIS Cut Line= 4
      1640244.64      6851955.58      1640916.48      6852419.10
      1641312.31      6852564.93      1642484.21      6852606.60
#Sta/Elev= 30
  3719.6 1853.22  3729.4 1854.15  3735.5 1852.75  3756.5 1853.61  3786.2 1852.42
  3908.6 1854.11  4347.4 1845.59  4404.1 1845.79  4806.7 1838.89  4867.6 1839.40
  4892.7 1842.58  4898.1 1840.96  4923.2 1838.41  4928.6 1835.39  4948.3 1831.39
  4960.0 1831.34  4960.5 1830.84  4980.7 1831.34  5020.4 1831.81  5050.4 1841.55
  5070.4 1842.52  5140.5 1843.11  5170.5 1841.50  5570.7 1843.81  5720.8 1847.49
  5770.9 1849.65  5850.9 1857.57  5961.0 1862.47  6027.5 1868.74  6130.3 1872.02
#Mann=3,-1,0
  3719.6    0.05       0  4960.0    0.05       0  4980.7    0.05       0
Bank Sta=4960,4980.7
Exp/Cntr=0.3,0.1

Type RM Length L Ch R = 1,151934,286,286,286
BEGIN DESCRIPTION:
Deadman Creek 189.0
END DESCRIPTION:
XS GIS Cut Line= 3
      1640057.09      6852215.97      1641171.69      6852695.14
      1642429.96      6852962.99
#Sta/Elev= 30
  3765.1 1859.15  3804.6 1856.27  3909.6 1852.31  3956.7 1846.88  3991.4 1844.99
  4009.3 1847.76  4032.8 1848.68  4266.5 1845.87  4389.6 1846.28  4503.0 1845.49
  4633.6 1843.02  4793.6 1841.43  4905.7 1837.69  4969.3 1838.43  4974.7 1837.04
  5002.2 1835.30  5006.4 1834.03  5006.9 1833.53  5027.1 1834.03  5032.8 1835.93
  5043.1 1836.70  5110.8 1837.77  5124.9 1838.79  5298.7 1839.51  5497.2 1841.69
  5574.7 1843.54  5901.9 1847.63  6055.2 1851.22  6177.9 1852.26  6264.8 1854.03
#Mann=3,-1,0
  3765.1    0.05       0  5006.4    0.05       0  5027.1    0.05       0
Bank Sta=5006.4,5027.1
Exp/Cntr=0.3,0.1

Type RM Length L Ch R = 1,151648,477,477,477
BEGIN DESCRIPTION:
Mapping XS d775804b
END DESCRIPTION:
XS GIS Cut Line= 4
      1640072.72      6852413.89      1640833.15      6852861.81
      1641406.06      6853064.93      1642170.80      6853200.19
#Sta/Elev= 30
  3846.1 1859.47  3902.2 1855.43  4046.6 1851.08  4083.7 1849.05  4099.4 1847.11
  4142.3 1843.89  4185.3 1842.22  4216.5 1841.99  4259.4 1843.64  4275.1 1843.34
  4333.7 1844.88  4675.2 1842.67  4783.7 1840.09  4836.7 1837.27  4857.9 1834.74
  4868.5 1834.53  4883.1 1834.85  4900.4 1837.13  4944.9 1838.42  4953.4 1835.78
  4970.5 1833.32  5016.5 1831.82  5017.0 1831.32  5037.3 1831.82  5038.3 1833.05
  5048.9 1833.37  5080.7 1837.52  5155.7 1839.38  5500.3 1841.76  6113.1 1850.02
#Mann=3,-1,0
  3846.1    0.05       0  5016.5    0.05       0  5037.3    0.05       0
Bank Sta=5016.5,5037.3
Exp/Cntr=0.3,0.1

Type RM Length L Ch R = 1,151171,588,588,588
BEGIN DESCRIPTION:
Deadman Creek 188.0
END DESCRIPTION:
XS GIS Cut Line= 3
      1640490.00      6852753.98      1640955.00      6853388.00
      1641510.84      6853403.02
#Sta/Elev= 30
  4208.2 1843.21  4257.8 1842.82  4278.6 1843.42  4287.1 1842.92  4429.1 1842.23
  4558.7 1840.49  4679.9 1838.06  4715.4 1836.87  4758.8 1834.40  4836.6 1836.63
  4901.5 1837.03  4916.1 1836.19  4922.3 1834.66  4937.0 1833.57  4951.6 1833.34
  4966.3 1834.12  4980.9 1832.49  4984.8 1829.46  4985.2 1828.96  5001.0 1828.96
  5001.4 1829.46  5034.5 1832.94  5054.5 1836.02  5064.5 1835.67  5074.5 1836.98
  5084.5 1837.32  5114.5 1837.20  5134.5 1836.43  5404.6 1838.89  5550.5 1840.87
#Mann=3,-1,0
  4208.2    0.05       0  4984.8    0.05       0  5001.4    0.05       0
Bank Sta=4984.8,5001.4
Exp/Cntr=0.3,0.1

Type RM Length L Ch R = 1,150583,504,504,504
BEGIN DESCRIPTION:
Mapping XS 5685a17e
END DESCRIPTION:
XS GIS Cut Line= 3
      1640044.48      6853256.96      1640617.39      6853751.74
      1641153.81      6853918.39
#Sta/Elev= 30
  4402.2 1863.53  4410.5 1862.18  4417.1 1862.49  4424.7 1860.73  4431.3 1860.87
  4453.2 1857.44  4459.8 1857.66  4481.7 1854.64  4488.4 1854.74  4502.6 1851.41
  4559.6 1845.87  4580.5 1844.85  4594.8 1842.83  4799.9 1835.78  4864.6 1834.60
  4956.7 1834.98  4971.0 1833.00  4973.7 1828.19  4974.2 1827.69  4994.8 1828.19
  4998.5 1829.83  5027.0 1830.10  5063.1 1832.23  5098.2 1832.34  5141.0 1834.50
  5195.2 1833.96  5298.2 1835.41  5303.4 1834.74  5355.6 1836.15  5720.9 1838.78
#Mann=3,-1,0
  4402.2    0.05       0  4973.7    0.05       0  4994.8    0.05       0
Bank Sta=4973.7,4994.8
Exp/Cntr=0.3,0.1

Type RM Length L Ch R = 1,150079,542,542,542
BEGIN DESCRIPTION:
Deadman Creek 186.0
END DESCRIPTION:
XS GIS Cut Line= 3
      1639804.99      6853788.00      1640155.00      6853988.00
      1641705.02      6855088.01
#Sta/Elev= 30
  4595.7 1887.90  4641.1 1886.82  4749.0 1874.26  4764.9 1870.82  4823.9 1862.84
  4837.6 1858.73  4867.1 1845.41  4904.5 1833.84  4918.2 1831.49  4941.2 1833.32
  4963.5 1832.93  4985.1 1829.16  4995.9 1825.20  5001.9 1825.20  5006.2 1822.99
  5014.0 1821.71  5014.5 1821.21  5040.2 1821.71  5041.9 1825.81  5048.0 1825.38
  5071.4 1831.36  5113.2 1832.93  5543.8 1833.35  5959.6 1838.31  6283.2 1845.32
  6339.7 1847.19  6425.8 1854.39  6633.7 1862.70  6820.7 1873.77  6899.5 1876.92
#Mann=3,-1,0
  4595.7    0.05       0  5014.0    0.05       0  5040.2    0.05       0
Bank Sta=5014,5040.2
Exp/Cntr=0.3,0.1

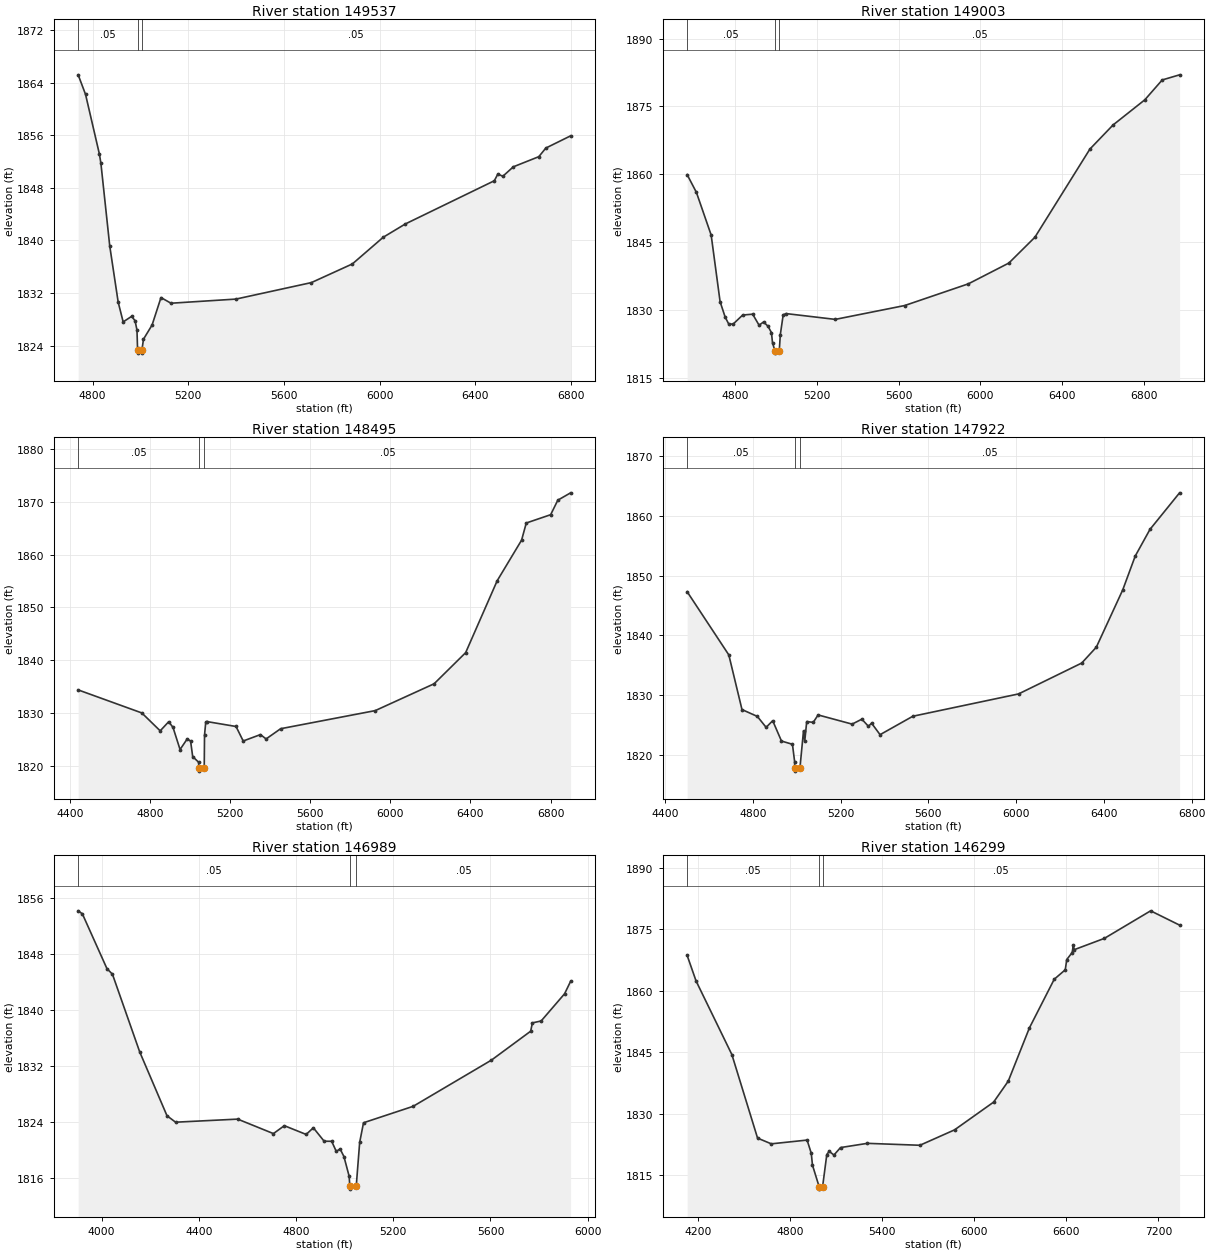
Type RM Length L Ch R = 1,149537,534,534,534
BEGIN DESCRIPTION:
Deadman Creek 185.0
END DESCRIPTION:
XS GIS Cut Line= 3
      1639700.71      6854277.77      1639905.00      6854438.00
      1641357.00      6855501.76
#Sta/Elev= 30
  4739.4 1865.18  4770.3 1862.20  4828.2 1853.13  4834.5 1851.72  4871.5 1839.14
  4906.8 1830.60  4927.6 1827.60  4962.9 1828.44  4977.3 1827.79  4985.4 1826.35
  4987.9 1823.35  4988.2 1822.85  5005.9 1822.85  5006.2 1823.35  5012.6 1824.97
  5048.6 1827.13  5085.8 1831.30  5127.6 1830.44  5399.3 1831.07  5715.0 1833.58
  5886.4 1836.42  6015.5 1840.48  6107.9 1842.50  6480.0 1849.07  6494.7 1850.09
  6515.5 1849.75  6559.5 1851.19  6666.0 1852.73  6695.4 1854.04  6799.0 1855.90
#Mann=3,-1,0
  4739.4    0.05       0  4987.9    0.05       0  5006.2    0.05       0
Bank Sta=4987.9,5006.2
Exp/Cntr=0.3,0.1

Type RM Length L Ch R = 1,149003,508,508,508
BEGIN DESCRIPTION:
Deadman Creek 184.0
END DESCRIPTION:
XS GIS Cut Line= 3
      1639504.99      6854487.98      1639655.00      6854888.00
      1641054.99      6856287.99
#Sta/Elev= 30
  4566.2 1859.95  4611.6 1856.02  4683.7 1846.60  4727.3 1831.90  4752.2 1828.47
  4769.1 1827.00  4790.5 1826.92  4837.7 1828.94  4886.6 1829.13  4917.8 1826.70
  4940.0 1827.41  4961.4 1826.47  4978.3 1825.07  4983.6 1822.81  4995.5 1821.03
  4995.9 1820.53  5016.6 1821.03  5021.7 1824.60  5035.8 1828.99  5050.0 1829.26
  5290.4 1827.98  5629.8 1831.04  5940.9 1835.83  6138.9 1840.42  6266.2 1846.12
  6534.9 1865.58  6648.0 1870.90  6803.6 1876.47  6888.5 1880.85  6973.3 1881.98
#Mann=3,-1,0
  4566.2    0.05       0  4995.5    0.05       0  5016.6    0.05       0
Bank Sta=4995.5,5016.6
Exp/Cntr=0.3,0.1

Type RM Length L Ch R = 1,148495,573,573,573
BEGIN DESCRIPTION:
Deadman Creek 183.0
END DESCRIPTION:
XS GIS Cut Line= 3
      1638846.30      6854707.54      1639255.00      6855088.00
      1640804.97      6856187.98
#Sta/Elev= 30
  4441.0 1834.43  4758.8 1830.08  4850.6 1826.70  4893.1 1828.42  4914.6 1827.35
  4949.8 1823.17  4985.5 1825.17  5002.4 1824.77  5012.9 1821.83  5042.4 1820.78
  5043.9 1819.59  5044.4 1819.09  5070.5 1819.59  5072.0 1825.89  5078.1 1828.34
  5085.2 1828.44  5229.4 1827.52  5265.1 1824.78  5351.2 1825.99  5379.5 1825.17
  5452.1 1827.10  5924.5 1830.52  6218.5 1835.59  6376.0 1841.47  6533.4 1855.05
  6655.2 1862.71  6678.6 1865.95  6800.4 1867.52  6836.1 1870.26  6900.0 1871.65
#Mann=3,-1,0
  4441.0    0.05       0  5043.9    0.05       0  5070.5    0.05       0
Bank Sta=5043.9,5070.5
Exp/Cntr=0.3,0.1

Type RM Length L Ch R = 1,147922,933,933,933
BEGIN DESCRIPTION:
Deadman Creek 182.0
END DESCRIPTION:
XS GIS Cut Line= 3
      1638505.02      6855388.00      1639005.00      6855388.00
      1640555.04      6856188.02
#Sta/Elev= 30
  4500.8 1847.30  4690.8 1836.70  4750.8 1827.54  4820.8 1826.39  4860.8 1824.56
  4890.8 1825.67  4930.8 1822.26  4980.8 1821.72  4990.8 1818.79  4991.0 1817.72
  4991.5 1817.22  5014.9 1817.72  5031.2 1823.99  5036.8 1822.21  5045.8 1825.53
  5075.5 1825.39  5097.7 1826.64  5252.7 1825.10  5297.1 1825.93  5327.1 1824.73
  5341.4 1825.26  5380.1 1823.33  5529.5 1826.42  6011.3 1830.16  6299.3 1835.34
  6365.8 1838.00  6486.2 1847.61  6543.0 1853.27  6610.0 1857.73  6745.1 1863.87
#Mann=3,-1,0
  4500.8    0.05       0  4991.0    0.05       0  5014.9    0.05       0
Bank Sta=4991,5014.9
Exp/Cntr=0.3,0.1

Type RM Length L Ch R = 1,146989,690,690,690
BEGIN DESCRIPTION:
Deadman Creek 181.0
END DESCRIPTION:
XS GIS Cut Line= 3
      1638289.43      6855632.67      1639218.56      6856106.60
      1640071.39      6856595.41
#Sta/Elev= 30
  3903.8 1854.18  3921.1 1853.75  4022.3 1845.91  4044.8 1845.12  4157.0 1834.01
  4269.3 1824.88  4304.6 1823.96  4560.1 1824.40  4707.1 1822.33  4752.0 1823.46
  4841.8 1822.21  4871.4 1823.16  4915.8 1821.24  4946.8 1821.23  4965.8 1819.78
  4981.4 1820.14  4997.2 1819.05  5018.8 1816.22  5021.2 1814.89  5021.7 1814.39
  5048.0 1814.89  5062.0 1821.08  5077.8 1823.88  5282.1 1826.23  5604.3 1832.84
  5765.5 1836.97  5772.6 1838.16  5808.6 1838.43  5905.0 1842.32  5929.8 1844.10
#Mann=3,-1,0
  3903.8    0.05       0  5021.2    0.05       0  5048.0    0.05       0
Bank Sta=5021.2,5048
Exp/Cntr=0.3,0.1

Type RM Length L Ch R = 1,146299,567,567,567
BEGIN DESCRIPTION:
Deadman Creek 180.0
END DESCRIPTION:
XS GIS Cut Line= 3
      1638005.03      6855788.02      1638755.00      6856238.00
      1640755.01      6857438.00
#Sta/Elev= 30
  4130.8 1868.67  4189.1 1862.40  4422.3 1844.43  4589.5 1824.04  4678.9 1822.64
  4912.1 1823.56  4939.3 1820.33  4947.1 1817.44  4991.3 1812.08  4991.7 1811.58
  5012.7 1812.08  5040.4 1820.03  5055.9 1820.81  5087.0 1819.91  5129.8 1821.73
  5304.7 1822.76  5646.8 1822.29  5872.3 1826.05  6126.9 1832.83  6222.1 1837.95
  6360.1 1850.97  6521.5 1862.83  6593.4 1865.14  6603.1 1867.64  6638.1 1869.34
  6645.9 1871.13  6651.7 1870.05  6848.0 1872.81  7149.3 1879.54  7337.8 1876.05
#Mann=3,-1,0
  4130.8    0.05       0  4991.3    0.05       0  5012.7    0.05       0
Bank Sta=4991.3,5012.7
Exp/Cntr=0.3,0.1