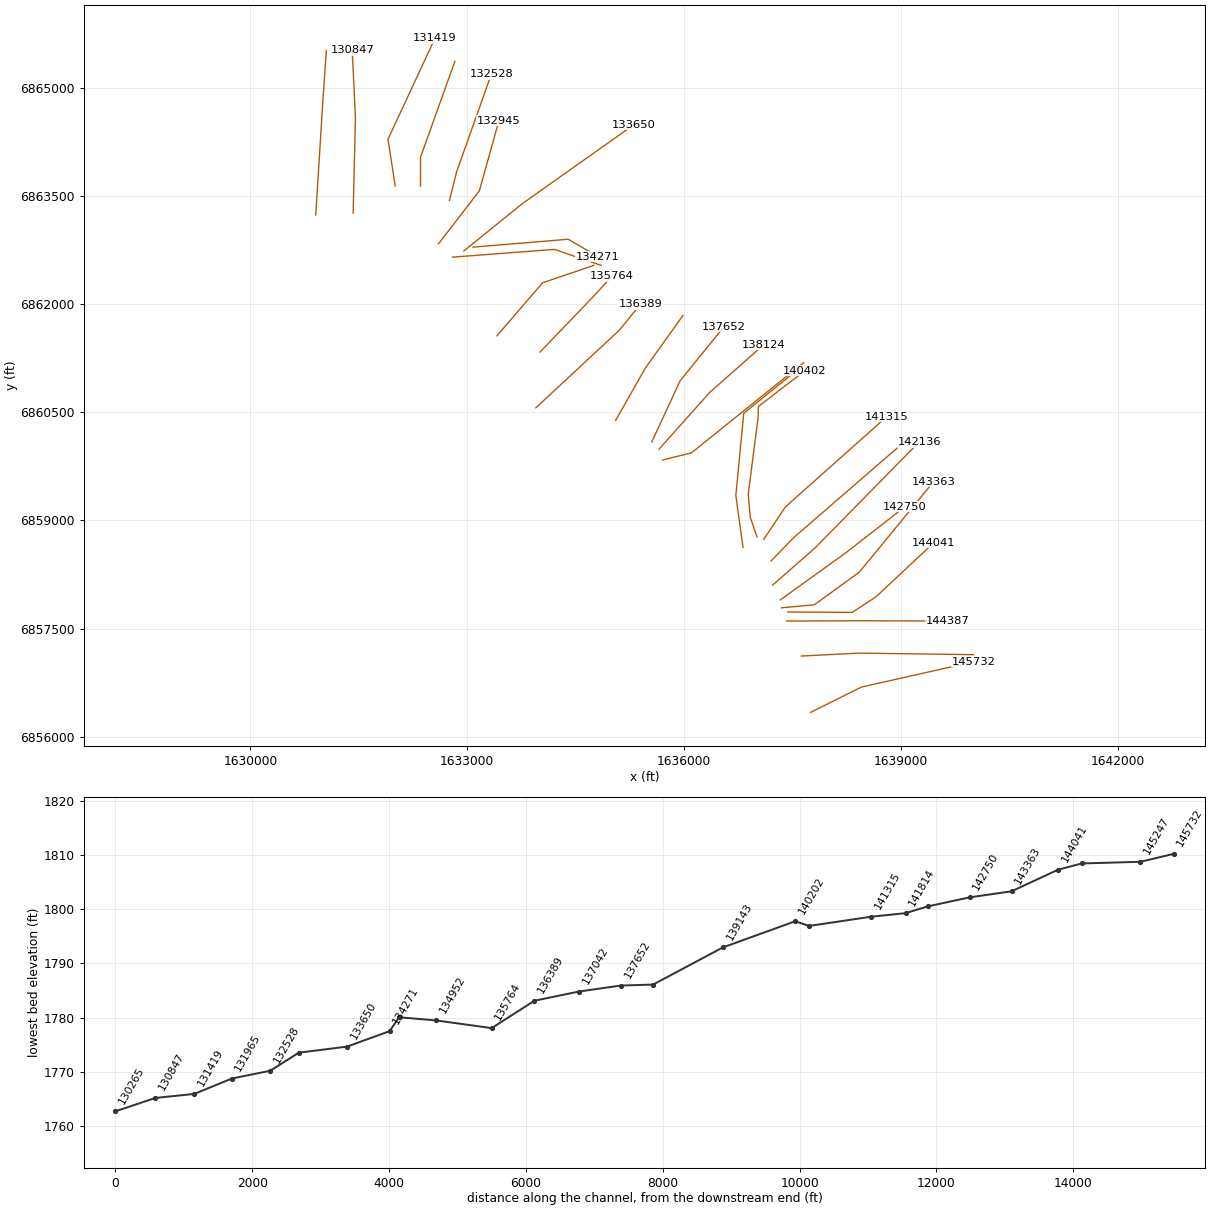
HEC-RAS study Deadman Creek.prj: Deadman Creek Base Level Engineering

--- Deadman Creek.g01 (geometry) --- (continued)

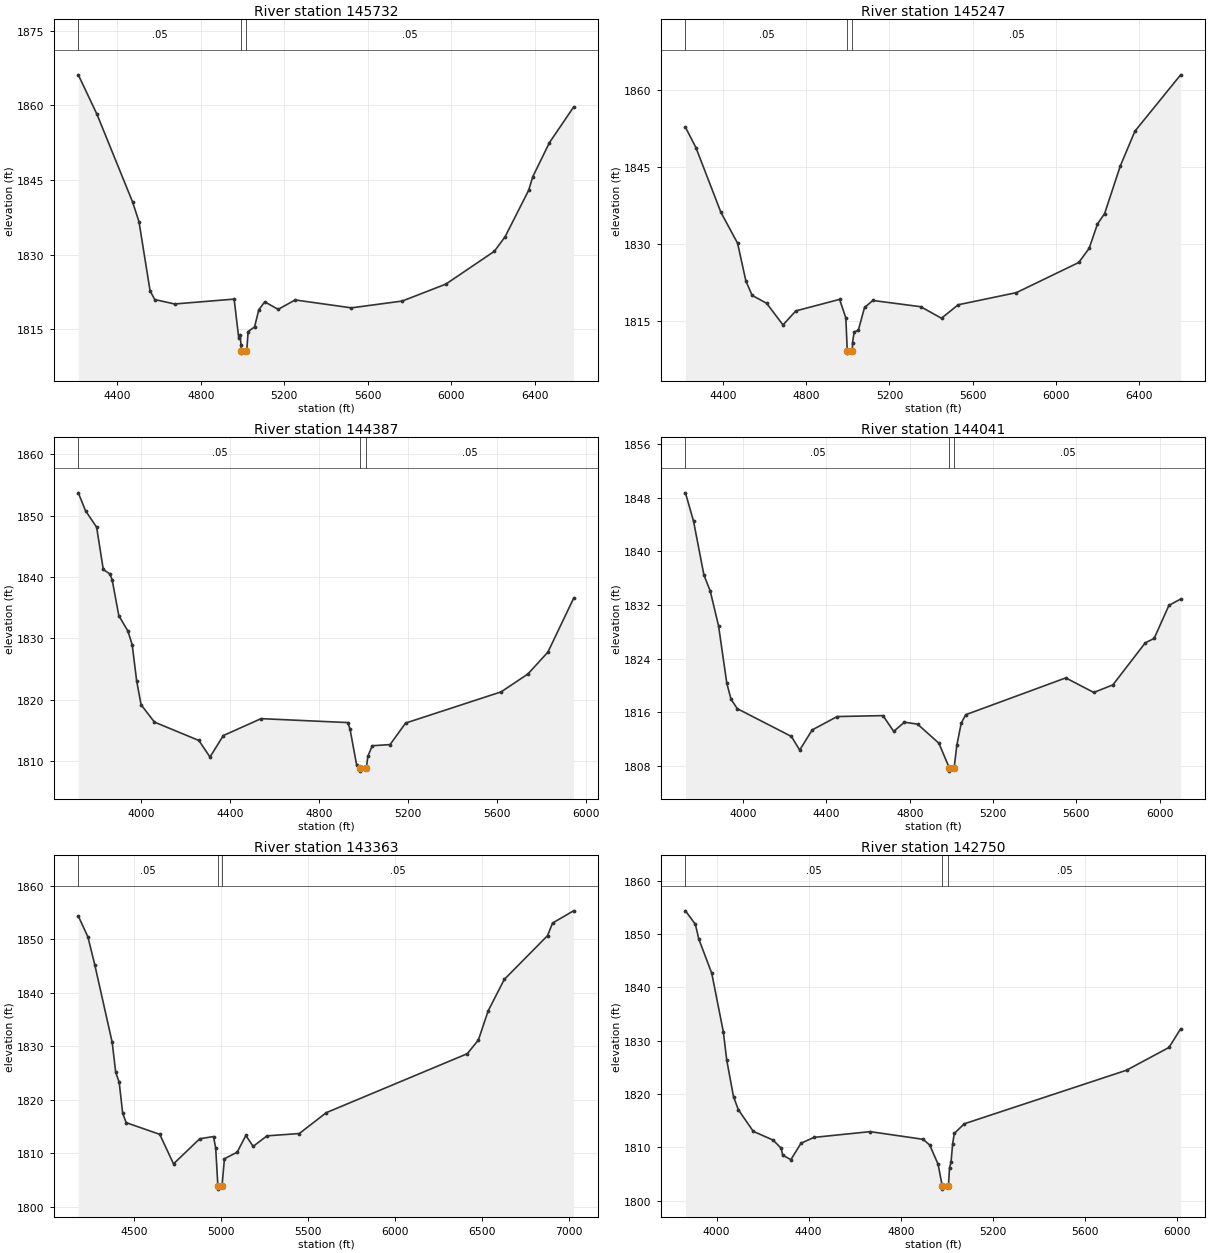
Type RM Length L Ch R = 1,145732,485,485,485
BEGIN DESCRIPTION:
Deadman Creek 179.0
END DESCRIPTION:
XS GIS Cut Line= 3
      1637754.99      6856338.00      1638455.00      6856688.00
      1640005.04      6857038.01
#Sta/Elev= 30
  4213.3 1866.12  4302.8 1858.18  4473.3 1840.56  4504.0 1836.59  4557.1 1822.69
  4579.5 1820.95  4674.5 1820.06  4959.6 1821.04  4982.0 1813.13  4987.5 1813.91
  4993.1 1811.79  4993.4 1810.68  4993.9 1810.18  5017.6 1810.68  5020.1 1810.76
  5026.7 1814.52  5057.4 1815.44  5077.9 1818.92  5106.5 1820.49  5170.2 1818.98
  5252.2 1820.87  5521.0 1819.28  5764.8 1820.65  5973.5 1824.05  6205.6 1830.64
  6256.9 1833.54  6369.7 1842.87  6390.2 1845.66  6469.3 1852.46  6585.0 1859.62
#Mann=3,-1,0
  4213.3    0.05       0  4993.4    0.05       0  5017.6    0.05       0
Bank Sta=4993.4,5017.6
Exp/Cntr=0.3,0.1

Type RM Length L Ch R = 1,145247,860,860,860
BEGIN DESCRIPTION:
Deadman Creek 178.0
END DESCRIPTION:
XS GIS Cut Line= 3
      1637624.69      6857119.16      1638424.13      6857159.58
      1640005.03      6857138.00
#Sta/Elev= 30
  4219.1 1852.68  4269.5 1848.72  4389.6 1836.12  4469.7 1830.12  4509.8 1822.76
  4539.8 1819.96  4609.9 1818.41  4688.1 1814.21  4750.1 1816.94  4960.4 1819.18
  4990.4 1815.58  4997.3 1809.22  4997.8 1808.72  5021.5 1809.22  5022.5 1810.73
  5030.4 1812.85  5050.4 1813.15  5080.4 1817.60  5120.4 1818.97  5350.5 1817.75
  5450.5 1815.51  5530.5 1818.13  5810.5 1820.49  6110.5 1826.36  6160.5 1829.11
  6200.5 1833.84  6234.9 1835.88  6310.5 1845.16  6380.6 1851.91  6600.6 1862.88
#Mann=3,-1,0
  4219.1    0.05       0  4997.3    0.05       0  5021.5    0.05       0
Bank Sta=4997.3,5021.5
Exp/Cntr=0.3,0.1

Type RM Length L Ch R = 1,144387,346,346,346
BEGIN DESCRIPTION:
Mapping XS 59463c89
END DESCRIPTION:
XS GIS Cut Line= 3
      1637422.65      6857604.19      1638437.60      6857608.68
      1639650.33      6857604.33
#Sta/Elev= 30
  3716.8 1853.69  3749.2 1850.79  3799.2 1848.10  3829.2 1841.22  3859.2 1840.48
  3869.2 1839.52  3899.2 1833.69  3939.2 1831.25  3959.2 1829.00  3979.2 1823.12
  3999.2 1819.21  4059.2 1816.39  4259.2 1813.40  4309.2 1810.70  4369.2 1814.20
  4539.2 1816.95  4929.2 1816.31  4939.2 1815.23  4969.2 1809.35  4985.7 1808.91
  4986.2 1808.41  5012.7 1808.91  5019.2 1810.81  5039.2 1812.54  5119.2 1812.73
  5189.2 1816.23  5619.2 1821.31  5739.2 1824.21  5829.2 1827.77  5944.5 1836.50
#Mann=3,-1,0
  3716.8    0.05       0  4985.7    0.05       0  5012.7    0.05       0
Bank Sta=4985.7,5012.7
Exp/Cntr=0.3,0.1

Type RM Length L Ch R = 1,144041,678,678,678
BEGIN DESCRIPTION:
Deadman Creek 177.0
END DESCRIPTION:
XS GIS Cut Line= 4
      1637436.08      6857729.94      1638328.76      6857724.69
      1638655.00      6857938.00      1639455.03      6858688.02
#Sta/Elev= 30
  3722.4 1848.71  3761.3 1844.48  3811.3 1836.46  3841.3 1834.09  3881.3 1828.92
  3921.3 1820.31  3941.3 1817.97  3971.3 1816.56  4231.3 1812.42  4271.3 1810.39
  4331.3 1813.39  4451.3 1815.38  4671.6 1815.52  4722.9 1813.17  4774.2 1814.54
  4837.6 1814.25  4940.0 1811.41  4989.8 1807.75  4990.2 1807.25  5013.3 1807.75
  5026.1 1811.08  5047.1 1814.37  5068.6 1815.65  5549.7 1821.14  5684.1 1818.97
  5775.9 1820.10  5931.7 1826.37  5974.2 1827.02  6045.0 1831.94  6101.5 1832.89
#Mann=3,-1,0
  3722.4    0.05       0  4989.8    0.05       0  5013.3    0.05       0
Bank Sta=4989.8,5013.3
Exp/Cntr=0.3,0.1

Type RM Length L Ch R = 1,143363,613,613,613
BEGIN DESCRIPTION:
Deadman Creek 176.0
END DESCRIPTION:
XS GIS Cut Line= 4
      1637350.81      6857788.32      1637805.43      6857830.12
      1638430.16      6858285.87      1639455.00      6859538.00
#Sta/Elev= 30
  4180.1 1854.37  4235.4 1850.48  4274.7 1845.26  4375.1 1830.74  4395.2 1825.14
  4415.3 1823.27  4435.4 1817.46  4455.4 1815.72  4648.5 1813.53  4727.7 1808.01
  4878.3 1812.70  4957.8 1813.12  4970.3 1810.94  4983.0 1803.78  4983.4 1803.28
  5006.5 1803.78  5020.4 1808.96  5093.8 1810.19  5143.6 1813.32  5185.7 1811.28
  5265.3 1813.25  5451.0 1813.68  5606.5 1817.59  6417.2 1828.62  6481.1 1831.19
  6537.0 1836.62  6629.6 1842.51  6878.7 1850.71  6907.4 1853.06  7028.0 1855.35
#Mann=3,-1,0
  4180.1    0.05       0  4983.0    0.03       0  5006.5    0.05       0
Bank Sta=4983,5006.5
Exp/Cntr=0.3,0.1

Type RM Length L Ch R = 1,142750,614,614,614
BEGIN DESCRIPTION:
Deadman Creek 175.0
END DESCRIPTION:
XS GIS Cut Line= 3
      1637334.35      6857898.32      1638243.07      6858553.14
      1639054.97      6859187.98
#Sta/Elev= 30
  3864.9 1854.33  3908.0 1851.81  3922.7 1849.07  3979.2 1842.62  4029.5 1831.64
  4044.2 1826.35  4073.6 1819.49  4094.5 1817.06  4159.5 1812.99  4245.4 1811.36
  4281.0 1809.81  4287.2 1808.54  4322.8 1807.68  4366.9 1810.77  4423.4 1811.86
  4666.9 1812.94  4897.1 1811.50  4925.7 1810.43  4962.1 1806.84  4980.5 1802.66
  4980.9 1802.16  5006.9 1802.66  5011.8 1806.14  5018.2 1807.16  5025.5 1810.70
  5032.6 1812.61  5076.0 1814.41  5780.5 1824.45  5965.0 1828.72  6015.6 1832.21
#Mann=3,-1,0
  3864.9    0.05       0  4980.5    0.05       0  5006.9    0.05       0
Bank Sta=4980.5,5006.9
Exp/Cntr=0.3,0.1

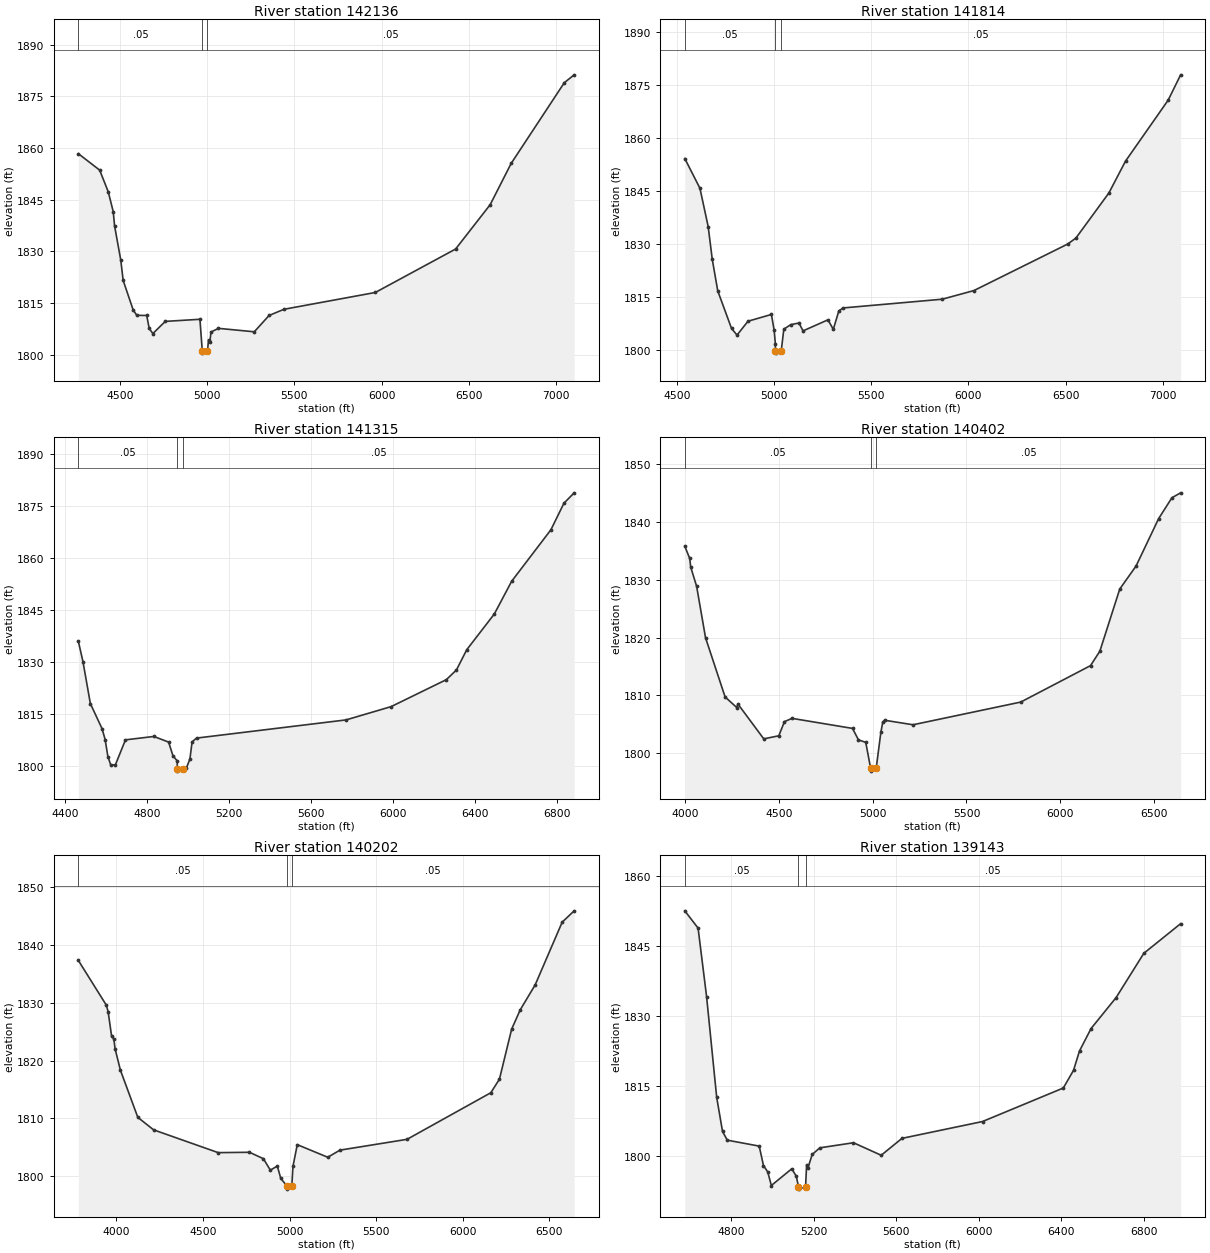
Type RM Length L Ch R = 1,142136,322,322,322
BEGIN DESCRIPTION:
Deadman Creek 174.0
END DESCRIPTION:
XS GIS Cut Line= 3
      1637227.43      6858103.21      1637810.99      6858615.50
      1639255.00      6860088.00
#Sta/Elev= 30
  4262.8 1858.37  4384.9 1853.60  4434.2 1847.29  4462.7 1841.53  4470.3 1837.41
  4505.4 1827.60  4519.6 1821.58  4576.5 1813.06  4597.4 1811.46  4654.3 1811.41
  4668.6 1807.65  4689.5 1806.17  4760.6 1809.70  4959.0 1810.31  4972.7 1800.99
  4973.2 1800.49  5002.1 1800.99  5008.3 1804.35  5015.9 1803.81  5022.5 1806.62
  5065.2 1807.68  5270.2 1806.68  5355.0 1811.42  5439.9 1813.21  5963.2 1818.09
  6422.9 1830.70  6620.9 1843.57  6741.0 1855.54  7045.2 1878.96  7101.7 1881.25
#Mann=3,-1,0
  4262.8    0.05       0  4972.7    0.05       0  5002.1    0.05       0
Bank Sta=4972.7,5002.1
Exp/Cntr=0.3,0.1

Type RM Length L Ch R = 1,141814,499,499,499
BEGIN DESCRIPTION:
Deadman Creek 173.0
END DESCRIPTION:
XS GIS Cut Line= 3
      1637205.02      6858438.02      1637530.42      6858771.84
      1639104.99      6860137.99
#Sta/Elev= 30
  4540.5 1854.25  4618.3 1845.85  4660.7 1835.04  4681.8 1825.76  4710.1 1816.83
  4780.9 1806.23  4809.2 1804.35  4865.7 1808.27  4986.1 1810.18  5000.2 1805.72
  5006.4 1801.93  5006.8 1799.75  5007.3 1799.25  5036.3 1799.75  5050.0 1806.03
  5085.2 1807.29  5127.9 1807.76  5148.8 1805.54  5277.0 1808.66  5304.5 1805.98
  5333.0 1811.19  5354.9 1812.02  5864.8 1814.49  6028.2 1816.94  6509.6 1830.06
  6552.4 1831.76  6722.3 1844.52  6807.8 1853.52  7027.2 1870.75  7091.3 1877.91
#Mann=3,-1,0
  4540.5    0.05       0  5006.8    0.05       0  5036.3    0.05       0
Bank Sta=5006.8,5036.3
Exp/Cntr=0.3,0.1

Type RM Length L Ch R = 1,141315,913,913,913
BEGIN DESCRIPTION:
Deadman Creek 172.0
END DESCRIPTION:
XS GIS Cut Line= 3
      1637105.01      6858738.01      1637405.00      6859188.00
      1638805.04      6860438.03
#Sta/Elev= 30
  4464.8 1836.03  4487.3 1830.18  4523.4 1818.08  4580.5 1810.82  4595.5 1807.71
  4609.0 1802.77  4622.5 1800.45  4645.1 1800.36  4694.6 1807.61  4832.9 1808.59
  4905.0 1806.97  4926.0 1803.07  4947.0 1801.53  4947.3 1799.10  4947.8 1798.60
  4976.8 1799.10  4992.1 1799.57  5009.0 1802.12  5019.4 1807.02  5041.1 1808.12
  5770.2 1813.36  5990.0 1817.19  6259.2 1824.96  6308.5 1827.75  6358.7 1833.58
  6493.3 1843.89  6577.7 1853.31  6769.2 1868.16  6832.7 1875.81  6882.5 1878.80
#Mann=3,-1,0
  4464.8    0.05       0  4947.3    0.05       0  4976.8    0.05       0
Bank Sta=4947.3,4976.8
Exp/Cntr=0.3,0.1

Type RM Length L Ch R = 1,140402,200,200,200
BEGIN DESCRIPTION:
Mapping XS 062d10f5
END DESCRIPTION:
XS GIS Cut Line= 6
      1637010.23      6858773.26      1636916.48      6859049.31
      1636890.44      6859367.02      1637025.86      6860424.31
      1637031.06      6860580.56      1637671.67      6861075.33
#Sta/Elev= 30
  3999.2 1835.84  4025.3 1833.73  4030.8 1832.22  4062.2 1828.90  4109.8 1819.98
  4213.9 1809.74  4276.6 1807.89  4281.9 1808.53  4419.9 1802.48  4500.1 1803.01
  4530.2 1805.46  4570.4 1806.03  4892.8 1804.29  4924.5 1802.31  4963.4 1801.87
  4989.4 1797.39  4989.9 1796.89  5019.0 1797.39  5044.0 1803.62  5054.1 1805.40
  5064.2 1805.70  5215.4 1804.92  5789.2 1808.85  6161.0 1815.16  6210.8 1817.66
  6316.9 1828.43  6403.7 1832.41  6524.1 1840.63  6594.9 1844.24  6641.2 1845.09
#Mann=3,-1,0
  3999.2    0.05       0  4989.4    0.05       0  5019.0    0.05       0
Bank Sta=4989.4,5019
Exp/Cntr=0.3,0.1

Type RM Length L Ch R = 1,140202,1059,1059,1059
BEGIN DESCRIPTION:
Mapping XS c33c0f91
END DESCRIPTION:
XS GIS Cut Line= 4
      1636817.53      6858627.40      1636718.56      6859346.18
      1636827.94      6860486.81      1637598.78      6861111.81
#Sta/Elev= 30
  3780.0 1837.31  3942.1 1829.55  3952.2 1828.42  3972.4 1824.16  3984.7 1823.76
  3992.6 1821.98  4022.9 1818.34  4123.6 1810.17  4214.7 1808.01  4587.8 1804.07
  4768.6 1804.13  4848.9 1803.02  4889.1 1801.04  4929.3 1801.75  4949.4 1799.60
  4986.3 1798.26  4986.8 1797.76  5013.0 1798.26  5019.7 1801.70  5044.6 1805.45
  5220.6 1803.27  5291.0 1804.50  5678.5 1806.37  6162.6 1814.43  6212.3 1816.78
  6282.7 1825.42  6332.3 1828.76  6418.5 1833.07  6574.6 1843.92  6643.8 1845.88
#Mann=3,-1,0
  3780.0    0.05       0  4986.3    0.05       0  5013.0    0.05       0
Bank Sta=4986.3,5013
Exp/Cntr=0.3,0.1

Type RM Length L Ch R = 1,139143,1019,1019,1019
BEGIN DESCRIPTION:
Deadman Creek 170.0
END DESCRIPTION:
XS GIS Cut Line= 3
      1635705.05      6859838.01      1636105.00      6859938.00
      1637655.00      6861188.00
#Sta/Elev= 30
  4575.3 1852.51  4639.7 1848.81  4680.9 1834.15  4729.9 1812.57  4758.2 1805.27
  4781.4 1803.41  4936.0 1802.14  4956.6 1797.98  4977.3 1796.62  4994.8 1793.70
  5093.9 1797.29  5116.0 1795.66  5126.4 1793.43  5127.1 1792.93  5160.7 1793.43
  5165.9 1798.17  5172.3 1797.50  5193.1 1800.36  5229.9 1801.77  5393.0 1802.86
  5527.4 1800.18  5628.1 1803.80  6018.4 1807.40  6410.2 1814.58  6459.8 1818.38
  6488.6 1822.51  6544.6 1827.31  6666.1 1833.94  6800.5 1843.42  6978.8 1849.76
#Mann=3,-1,0
  4575.3    0.05       0  5126.4    0.05       0  5160.7    0.05       0
Bank Sta=5126.4,5160.7
Exp/Cntr=0.3,0.1

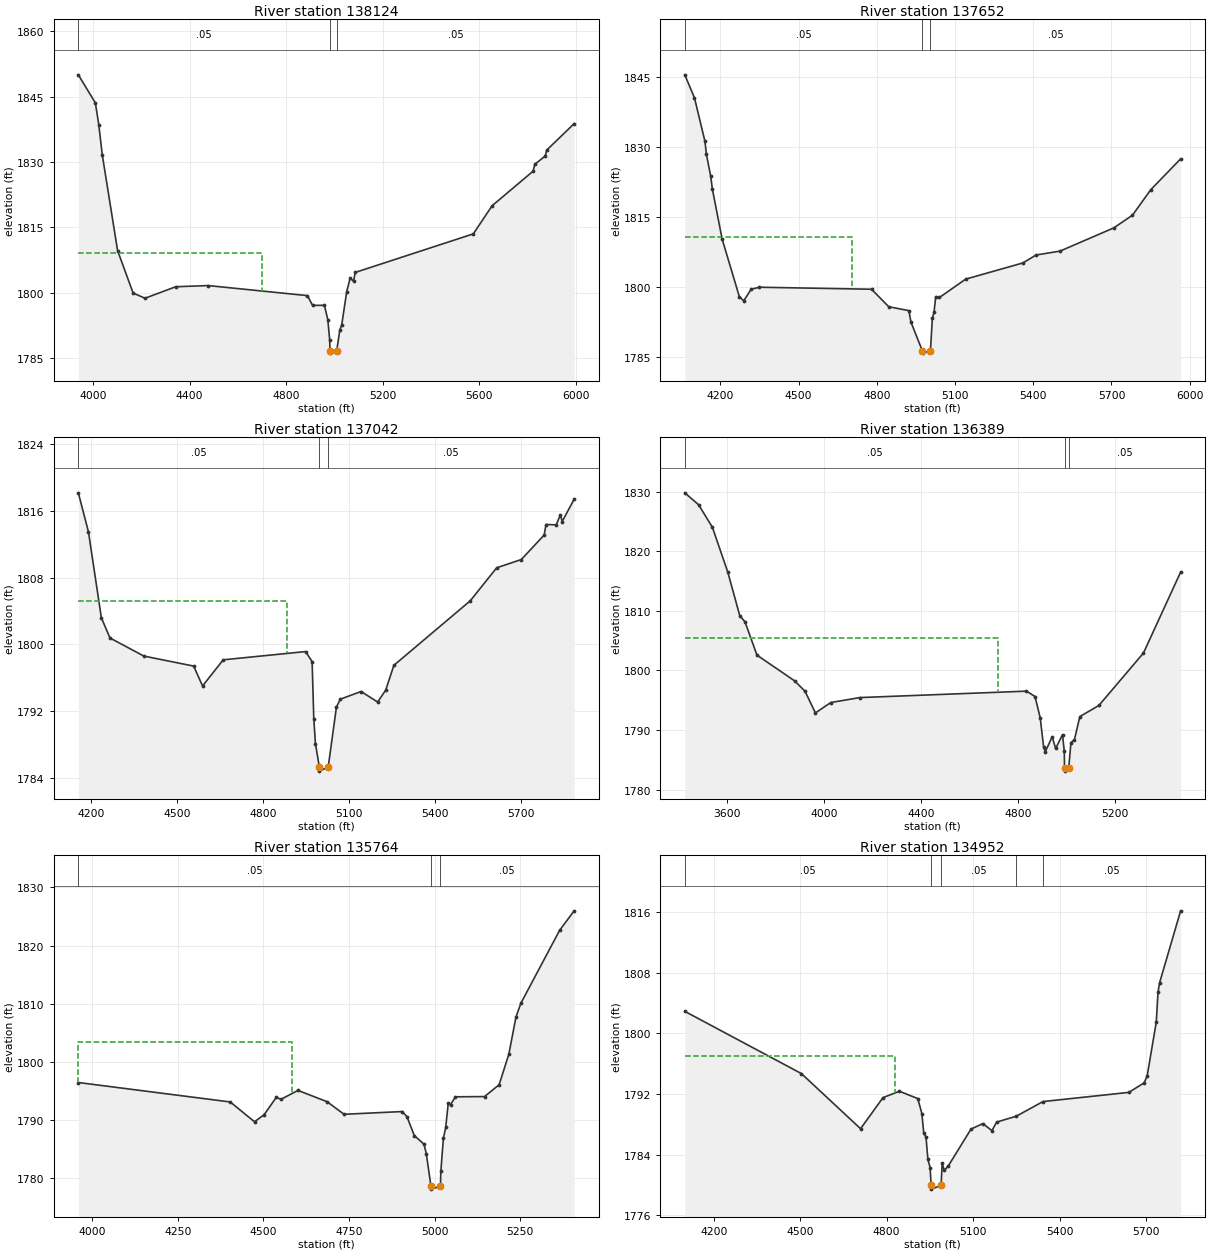
Type RM Length L Ch R = 1,138124,472,472,472
BEGIN DESCRIPTION:
Deadman Creek 169.0
END DESCRIPTION:
XS GIS Cut Line= 3
      1635655.01      6859988.02      1636361.07      6860779.85
      1637105.02      6861438.01
#Sta/Elev= 30
  3939.1 1850.02  4009.7 1843.57  4023.9 1838.55  4038.2 1831.66  4101.7 1809.65
  4166.1 1799.88  4215.4 1798.69  4342.5 1801.33  4477.1 1801.60  4888.4 1799.29
  4909.3 1797.06  4958.7 1797.06  4972.9 1793.70  4980.4 1789.13  4981.9 1786.58
  4982.5 1786.08  5009.4 1786.58  5022.6 1791.44  5030.1 1792.50  5051.0 1800.20
  5065.2 1803.31  5079.5 1802.62  5086.1 1804.62  5575.5 1813.48  5653.3 1819.94
  5823.1 1827.88  5830.6 1829.48  5873.1 1831.35  5879.9 1832.74  5993.3 1838.81
#Mann=3,-1,0
  3939.1    0.05       0  4981.9    0.05       0  5009.4    0.05       0
#XS Ineff=2,0
    0.00 4700.00 1809.04               0
Permanent Ineff=
       F       F
Bank Sta=4981.9,5009.4
Exp/Cntr=0.3,0.1

Type RM Length L Ch R = 1,137652,610,610,610
BEGIN DESCRIPTION:
Deadman Creek 168.0
END DESCRIPTION:
XS GIS Cut Line= 3
      1635555.02      6860088.04      1635947.72      6860937.79
      1636555.00      6861688.00
#Sta/Elev= 30
  4063.9 1845.36  4101.0 1840.44  4141.0 1831.18  4146.9 1828.34  4163.0 1823.77
  4169.8 1820.90  4207.1 1810.26  4273.2 1797.94  4290.0 1797.09  4318.4 1799.55
  4350.3 1799.98  4779.9 1799.55  4846.0 1795.81  4923.1 1794.98  4931.3 1792.51
  4974.8 1786.40  4975.4 1785.90  5005.9 1786.40  5013.1 1793.35  5019.5 1794.59
  5026.0 1797.96  5040.4 1797.79  5141.0 1801.71  5360.5 1805.17  5411.2 1806.87
  5502.4 1807.69  5708.6 1812.65  5780.5 1815.36  5850.9 1820.83  5965.2 1827.40
#Mann=3,-1,0
  4063.9    0.05       0  4974.8    0.05       0  5005.9    0.05       0
#XS Ineff=2,0
    0.00 4706.40 1810.74               0
Permanent Ineff=
       F       F
Bank Sta=4974.8,5005.9
Exp/Cntr=0.3,0.1

Type RM Length L Ch R = 1,137042,653,653,653
BEGIN DESCRIPTION:
Deadman Creek 167.0
END DESCRIPTION:
XS GIS Cut Line= 3
      1635055.00      6860388.01      1635466.30      6861113.96
      1635987.11      6861843.09
#Sta/Elev= 30
  4155.3 1818.18  4190.6 1813.50  4235.7 1803.19  4265.7 1800.77  4384.0 1798.60
  4557.6 1797.40  4588.9 1795.02  4661.0 1798.15  4948.3 1799.14  4971.2 1797.94
  4977.0 1791.08  4982.8 1788.11  4996.3 1785.30  4996.9 1784.80  5027.4 1785.30
  5056.1 1792.49  5069.7 1793.43  5142.1 1794.35  5199.9 1793.09  5228.1 1794.52
  5256.5 1797.49  5523.1 1805.23  5615.3 1809.19  5701.3 1810.18  5781.1 1813.12
  5787.4 1814.38  5823.0 1814.34  5837.7 1815.55  5843.9 1814.74  5885.7 1817.42
#Mann=3,-1,0
  4155.3    0.05       0  4996.3    0.03       0  5027.4    0.05       0
#XS Ineff=2,0
    0.00 4883.30 1805.24               0
Permanent Ineff=
       F       F
Bank Sta=4996.3,5027.4
Exp/Cntr=0.3,0.1

Type RM Length L Ch R = 1,136389,625,625,625
BEGIN DESCRIPTION:
Deadman Creek 166.0
END DESCRIPTION:
XS GIS Cut Line= 3
      1633950.65      6860561.85      1635105.00      6861638.00
      1635398.60      6861999.39
#Sta/Elev= 30
  3427.2 1829.83  3484.3 1827.82  3541.0 1824.04  3604.5 1816.50  3653.8 1809.20
  3675.3 1808.17  3724.6 1802.58  3880.5 1798.24  3923.0 1796.50  3965.5 1792.87
  4029.0 1794.62  4149.2 1795.45  4835.6 1796.53  4870.8 1795.63  4892.3 1792.03
  4906.4 1787.10  4913.3 1786.37  4941.6 1788.87  4955.8 1786.90  4984.1 1789.21
  4991.5 1786.40  4992.4 1783.60  4992.7 1783.10  5009.6 1783.60  5019.0 1787.88
  5033.4 1788.40  5055.7 1792.27  5134.0 1794.12  5317.8 1802.93  5471.0 1816.52
#Mann=3,-1,0
  3427.2    0.05       0  4992.4    0.05       0  5009.6    0.05       0
#XS Ineff=2,0
    0.00 4716.90 1805.42               0
Permanent Ineff=
       F       F
Bank Sta=4992.4,5009.6
Exp/Cntr=0.3,0.1

Type RM Length L Ch R = 1,135764,812,812,812
BEGIN DESCRIPTION:
Deadman Creek 165.0
END DESCRIPTION:
XS GIS Cut Line= 3
      1634009.50      6861336.18      1634728.06      6862086.18
      1635005.01      6862388.01
#Sta/Elev= 30
  3959.4 1796.41  4403.2 1793.06  4474.0 1789.65  4502.0 1790.86  4537.5 1793.84
  4551.6 1793.53  4601.0 1795.05  4685.9 1793.11  4735.6 1790.94  4905.1 1791.41
  4919.3 1790.53  4940.7 1787.28  4969.0 1785.79  4975.9 1784.14  4989.4 1778.55
  4990.1 1778.05  5017.1 1778.55  5018.3 1781.10  5025.7 1786.79  5032.5 1788.67
  5039.9 1792.82  5046.7 1792.61  5060.9 1793.95  5145.9 1793.99  5188.5 1796.02
  5216.9 1801.29  5237.8 1807.69  5252.0 1810.06  5365.5 1822.65  5407.7 1825.98
#Mann=3,-1,0
  3959.4    0.05       0  4989.4    0.05       0  5017.1    0.05       0
#XS Ineff=2,0
    0.00 4583.70 1803.45               0
Permanent Ineff=
       F       F
Bank Sta=4989.4,5017.1
Exp/Cntr=0.3,0.1

Type RM Length L Ch R = 1,134952,540,540,540
BEGIN DESCRIPTION:
Deadman Creek 164.0
END DESCRIPTION:
XS GIS Cut Line= 3
      1633412.23      6861560.76      1634045.43      6862297.25
      1634755.03      6862538.01
#Sta/Elev= 30
  4099.6 1802.92  4504.3 1794.71  4709.5 1787.44  4787.4 1791.54  4844.4 1792.38
  4908.1 1791.41  4922.3 1789.44  4928.9 1786.82  4936.6 1786.36  4943.2 1783.39
  4950.9 1782.31  4954.4 1779.97  4955.2 1779.47  4989.0 1779.97  4992.7 1782.86
  5000.3 1781.93  5014.5 1782.56  5092.8 1787.39  5133.8 1788.11  5165.5 1787.19
  5181.7 1788.31  5250.1 1789.09  5342.5 1791.02  5640.6 1792.23  5693.4 1793.48
  5704.0 1794.38  5735.7 1801.50  5741.7 1805.41  5746.9 1806.65  5820.2 1816.18
#Mann=5,-1,0
  4099.6    0.05       0  4954.4    0.03       0  4989.0    0.05       0
  5250.1    0.12       0  5342.5    0.05       0
#XS Ineff=2,0
    0.00 4827.30 1797.00               0
Permanent Ineff=
       F       F
Bank Sta=4954.4,4989
Exp/Cntr=0.3,0.1

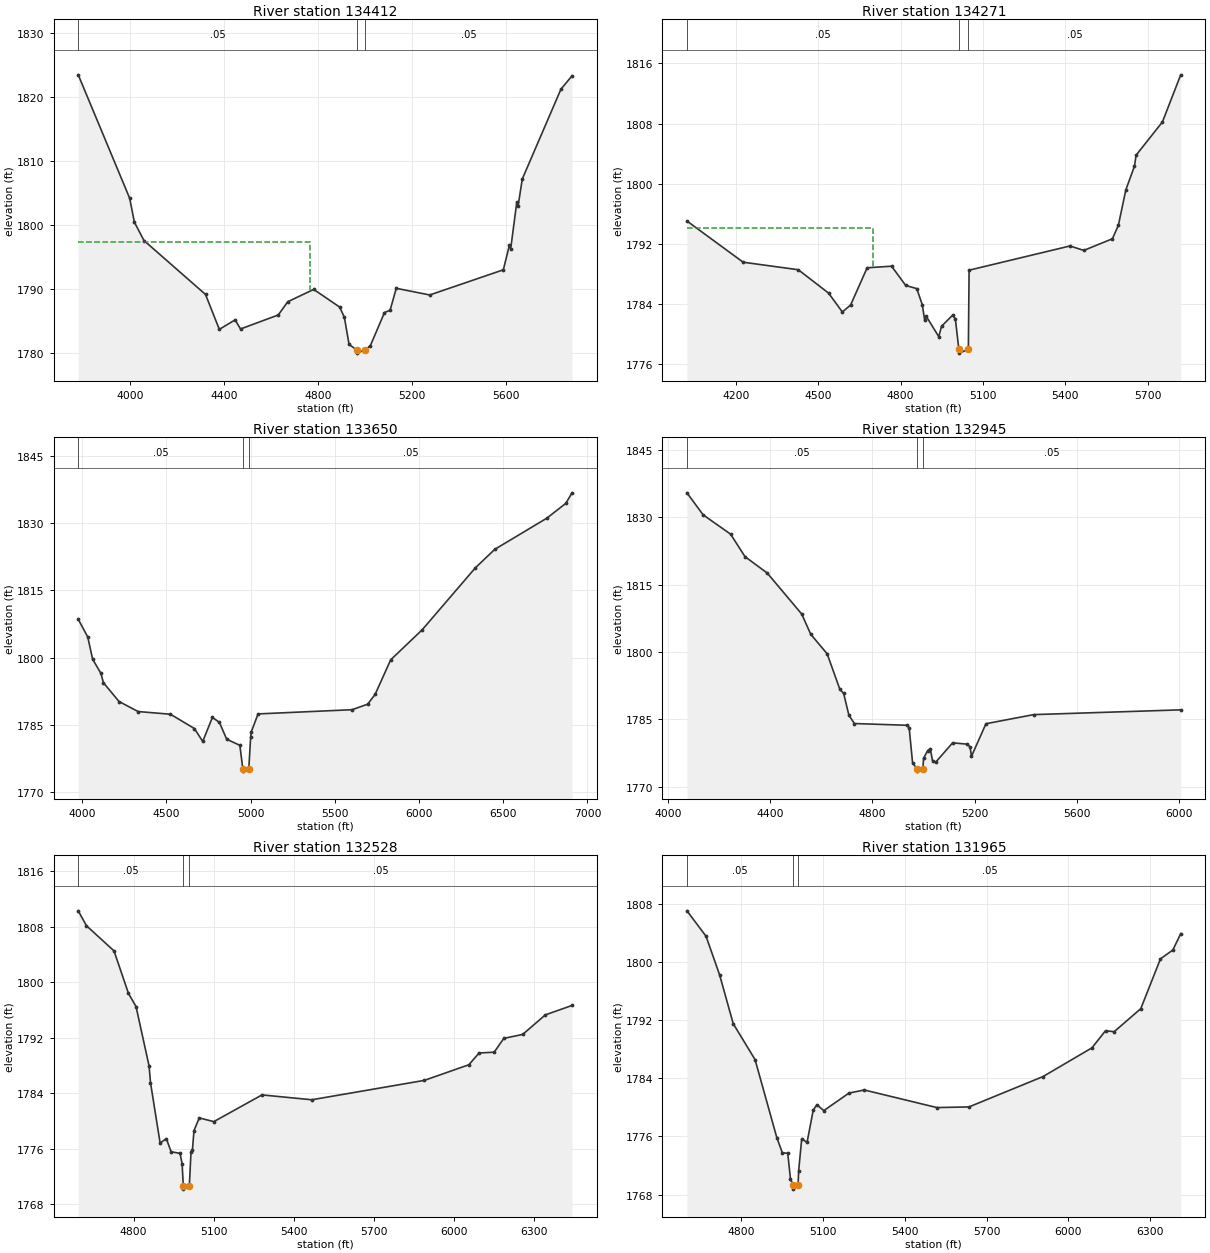
Type RM Length L Ch R = 1,134412,141,141,141
BEGIN DESCRIPTION:
Deadman Creek 163.0
END DESCRIPTION:
XS GIS Cut Line= 3
      1632796.96      6862652.04      1634207.11      6862759.82
      1634855.02      6862537.99
#Sta/Elev= 30
  3780.7 1823.50  3999.4 1804.23  4019.4 1800.49  4060.2 1797.63  4321.8 1789.21
  4380.5 1783.76  4447.5 1785.24  4470.7 1783.82  4631.2 1786.01  4671.3 1788.07
  4781.7 1790.00  4892.0 1787.24  4912.0 1785.65  4932.1 1781.40  4964.9 1780.55
  4965.6 1780.05  4999.5 1780.55  5022.4 1781.21  5082.5 1786.38  5106.5 1786.76
  5132.7 1790.17  5274.9 1789.13  5587.8 1793.06  5613.8 1796.91  5619.1 1796.34
  5645.1 1803.65  5650.4 1802.99  5668.4 1807.24  5832.8 1821.27  5879.8 1823.34
#Mann=3,-1,0
  3780.7    0.05       0  4964.9    0.03       0  4999.5    0.05       0
#XS Ineff=2,0
    0.00 4765.10 1797.39               0
Permanent Ineff=
       F       F
Bank Sta=4964.9,4999.5
Exp/Cntr=0.3,0.1

Type RM Length L Ch R = 1,134271,621,621,621
BEGIN DESCRIPTION:
Mapping XS c67fe878
END DESCRIPTION:
XS GIS Cut Line= 3
      1633080.90      6862791.04      1634398.59      6862900.41
      1634810.01      6862660.85
#Sta/Elev= 30
  4022.1 1795.05  4226.9 1789.57  4427.6 1788.57  4538.0 1785.46  4588.1 1782.95
  4618.2 1783.88  4678.4 1788.83  4767.4 1789.04  4818.9 1786.48  4859.1 1786.06
  4879.1 1783.93  4888.1 1781.83  4893.1 1782.41  4939.3 1779.67  4949.4 1781.06
  4989.5 1782.52  4999.6 1782.05  5012.4 1777.98  5013.1 1777.48  5047.0 1777.98
  5049.7 1788.51  5417.0 1791.73  5467.5 1791.14  5571.6 1792.69  5593.2 1794.46
  5620.5 1799.19  5652.0 1802.35  5657.8 1803.80  5753.7 1808.22  5820.4 1814.49
#Mann=3,-1,0
  4022.1    0.05       0  5012.4    0.05       0  5047.0    0.05       0
#XS Ineff=2,0
    0.00 4699.50 1794.18               0
Permanent Ineff=
       F       F
Bank Sta=5012.4,5047
Exp/Cntr=0.3,0.1

Type RM Length L Ch R = 1,133650,705,705,705
BEGIN DESCRIPTION:
Deadman Creek 162.0
END DESCRIPTION:
XS GIS Cut Line= 3
      1632955.01      6862738.01      1633755.00      6863388.00
      1635304.98      6864487.99
#Sta/Elev= 30
  3977.2 1808.54  4033.9 1804.56  4062.7 1799.62  4112.2 1796.44  4126.6 1794.39
  4219.3 1790.18  4332.8 1787.94  4524.5 1787.34  4666.8 1784.15  4716.3 1781.27
  4773.8 1786.63  4815.4 1785.52  4858.6 1781.75  4936.8 1780.40  4954.2 1775.14
  4955.0 1774.64  4989.8 1775.14  5000.8 1782.25  5004.7 1783.42  5044.8 1787.41
  5603.4 1788.35  5695.6 1789.59  5739.9 1791.78  5832.2 1799.49  6019.2 1806.19
  6334.1 1819.99  6449.8 1824.14  6758.5 1831.09  6871.8 1834.41  6908.6 1836.76
#Mann=3,-1,0
  3977.2    0.05       0  4954.2    0.05       0  4989.8    0.05       0
Bank Sta=4954.2,4989.8
Exp/Cntr=0.3,0.1

Type RM Length L Ch R = 1,132945,417,417,417
BEGIN DESCRIPTION:
Deadman Creek 161.0
END DESCRIPTION:
XS GIS Cut Line= 3
      1632605.03      6862838.04      1633169.69      6863572.69
      1633439.16      6864542.77
#Sta/Elev= 30
  4073.5 1835.38  4136.9 1830.49  4244.7 1826.18  4300.9 1821.19  4387.9 1817.55
  4523.0 1808.43  4558.3 1803.94  4622.6 1799.59  4672.5 1791.67  4687.0 1790.80
  4707.8 1785.92  4729.3 1784.10  4936.2 1783.71  4943.7 1783.11  4957.0 1775.36
  4974.4 1774.02  4974.9 1773.52  4997.2 1774.02  5000.1 1776.40  5016.0 1778.06
  5026.4 1778.49  5035.1 1775.82  5047.1 1775.48  5113.9 1779.81  5171.7 1779.51
  5182.0 1778.89  5187.6 1776.81  5244.3 1784.06  5431.1 1786.08  6006.9 1787.14
#Mann=3,-1,0
  4073.5    0.05       0  4974.4    0.05       0  4997.2    0.05       0
Bank Sta=4974.4,4997.2
Exp/Cntr=0.3,0.1

Type RM Length L Ch R = 1,132528,563,563,563
BEGIN DESCRIPTION:
Deadman Creek 160.0
END DESCRIPTION:
XS GIS Cut Line= 3
      1632755.00      6863437.99      1632855.00      6863838.00
      1633336.08      6865192.06
#Sta/Elev= 30
  4592.6 1810.27  4623.5 1808.12  4726.6 1804.50  4780.7 1798.38  4809.1 1796.48
  4858.0 1787.91  4863.2 1785.54  4899.3 1776.82  4922.5 1777.46  4940.5 1775.57
  4974.0 1775.34  4981.7 1773.84  4986.0 1770.69  4986.5 1770.19  5008.7 1770.69
  5015.0 1775.51  5020.3 1775.85  5026.1 1778.62  5045.9 1780.45  5100.4 1779.91
  5280.8 1783.76  5467.2 1783.06  5888.6 1785.85  6055.5 1788.10  6093.9 1789.80
  6150.3 1789.91  6186.5 1791.90  6257.2 1792.47  6342.1 1795.29  6441.9 1796.64
#Mann=3,-1,0
  4592.6    0.05       0  4986.0    0.05       0  5008.7    0.05       0
Bank Sta=4986,5008.7
Exp/Cntr=0.3,0.1

Type RM Length L Ch R = 1,131965,546,546,546
BEGIN DESCRIPTION:
Deadman Creek 159.0
END DESCRIPTION:
XS GIS Cut Line= 3
      1632355.00      6863637.98      1632355.00      6864038.00
      1632830.45      6865367.95
#Sta/Elev= 30
  4600.4 1807.07  4670.4 1803.58  4720.4 1798.24  4770.4 1791.52  4850.4 1786.59
  4930.4 1775.83  4950.4 1773.77  4970.4 1773.68  4980.4 1770.18  4990.1 1769.25
  4990.5 1768.75  5008.3 1769.25  5010.5 1771.29  5021.7 1775.69  5041.3 1775.18
  5064.1 1779.65  5077.4 1780.37  5102.8 1779.56  5195.2 1781.98  5251.5 1782.40
  5517.9 1779.98  5635.7 1780.07  5907.4 1784.25  6086.8 1788.20  6136.7 1790.56
  6168.6 1790.43  6266.2 1793.60  6338.5 1800.46  6384.0 1801.68  6412.8 1803.93
#Mann=3,-1,0
  4600.4    0.05       0  4990.1    0.05       0  5008.3    0.05       0
Bank Sta=4990.1,5008.3
Exp/Cntr=0.3,0.1

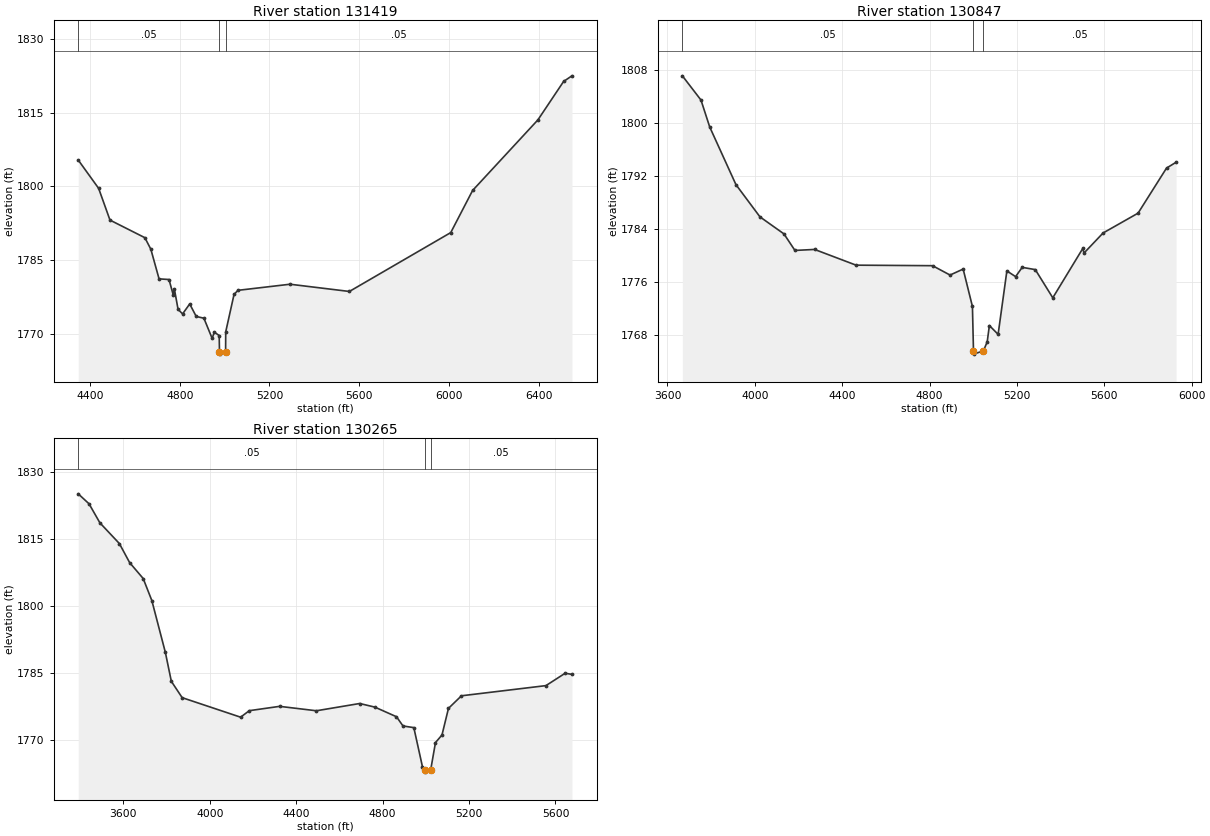
Type RM Length L Ch R = 1,131419,572,572,572
BEGIN DESCRIPTION:
Deadman Creek 158.0
END DESCRIPTION:
XS GIS Cut Line= 3
      1632005.00      6863638.01      1631905.00      6864288.00
      1632555.01      6865688.03
#Sta/Elev= 30
  4347.5 1805.38  4438.5 1799.62  4489.1 1793.17  4644.7 1789.59  4671.3 1787.24
  4707.9 1781.22  4752.2 1781.09  4771.2 1777.95  4776.2 1779.16  4792.7 1775.01
  4812.9 1774.10  4844.5 1776.12  4873.6 1773.58  4907.8 1773.22  4944.4 1769.14
  4954.5 1770.38  4976.0 1769.70  4977.3 1766.42  4977.9 1765.92  5004.6 1766.42
  5005.1 1770.45  5042.2 1778.06  5059.6 1778.89  5291.8 1780.13  5556.4 1778.66
  6008.4 1790.63  6105.8 1799.19  6397.1 1813.55  6511.6 1821.36  6548.7 1822.50
#Mann=3,-1,0
  4347.5    0.05       0  4977.3    0.05       0  5004.6    0.05       0
Bank Sta=4977.3,5004.6
Exp/Cntr=0.3,0.1

Type RM Length L Ch R = 1,130847,582,582,582
BEGIN DESCRIPTION:
Deadman Creek 157.0
END DESCRIPTION:
XS GIS Cut Line= 3
      1631422.71      6863262.80      1631455.00      6864588.00
      1631409.23      6865521.78
#Sta/Elev= 30
  3668.2 1807.12  3753.4 1803.47  3793.4 1799.41  3913.5 1790.72  4023.5 1785.86
  4133.5 1783.29  4183.6 1780.80  4273.6 1780.95  4463.6 1778.58  4813.7 1778.50
  4893.8 1777.09  4953.8 1777.99  4996.3 1772.35  5001.1 1765.67  5002.1 1765.17
  5046.6 1765.67  5063.9 1767.01  5073.9 1769.48  5113.9 1768.15  5154.0 1777.71
  5194.0 1776.85  5224.1 1778.25  5284.1 1777.91  5364.2 1773.66  5502.0 1781.12
  5507.0 1780.40  5594.5 1783.43  5754.7 1786.42  5884.9 1793.21  5928.7 1794.09
#Mann=3,-1,0
  3668.2    0.05       0  5001.1    0.05       0  5046.6    0.05       0
Bank Sta=5001.1,5046.6
Exp/Cntr=0.3,0.1

Type RM Length L Ch R = 1,130265,552,552,552
BEGIN DESCRIPTION:
Deadman Creek 156.0
END DESCRIPTION:
XS GIS Cut Line= 3
      1630905.00      6863237.96      1631005.00      6864838.00
      1631051.89      6865518.02
#Sta/Elev= 30
  3391.3 1825.12  3441.4 1822.88  3491.5 1818.62  3581.7 1813.97  3629.3 1809.69
  3691.9 1806.13  3732.0 1801.18  3794.6 1789.55  3822.2 1783.07  3872.3 1779.41
  4142.8 1775.03  4182.9 1776.49  4323.2 1777.46  4493.5 1776.47  4693.9 1778.10
  4764.0 1777.29  4864.2 1775.13  4894.3 1773.06  4944.4 1772.69  4984.4 1763.90
  4995.0 1763.21  4995.6 1762.71  5022.4 1763.21  5044.6 1769.34  5074.7 1771.04
  5104.7 1777.01  5164.9 1779.83  5555.8 1782.11  5644.8 1784.89  5676.1 1784.63
#Mann=3,-1,0
  3391.3    0.05       0  4995.0    0.05       0  5022.4    0.05       0
Bank Sta=4995,5022.4
Exp/Cntr=0.3,0.1