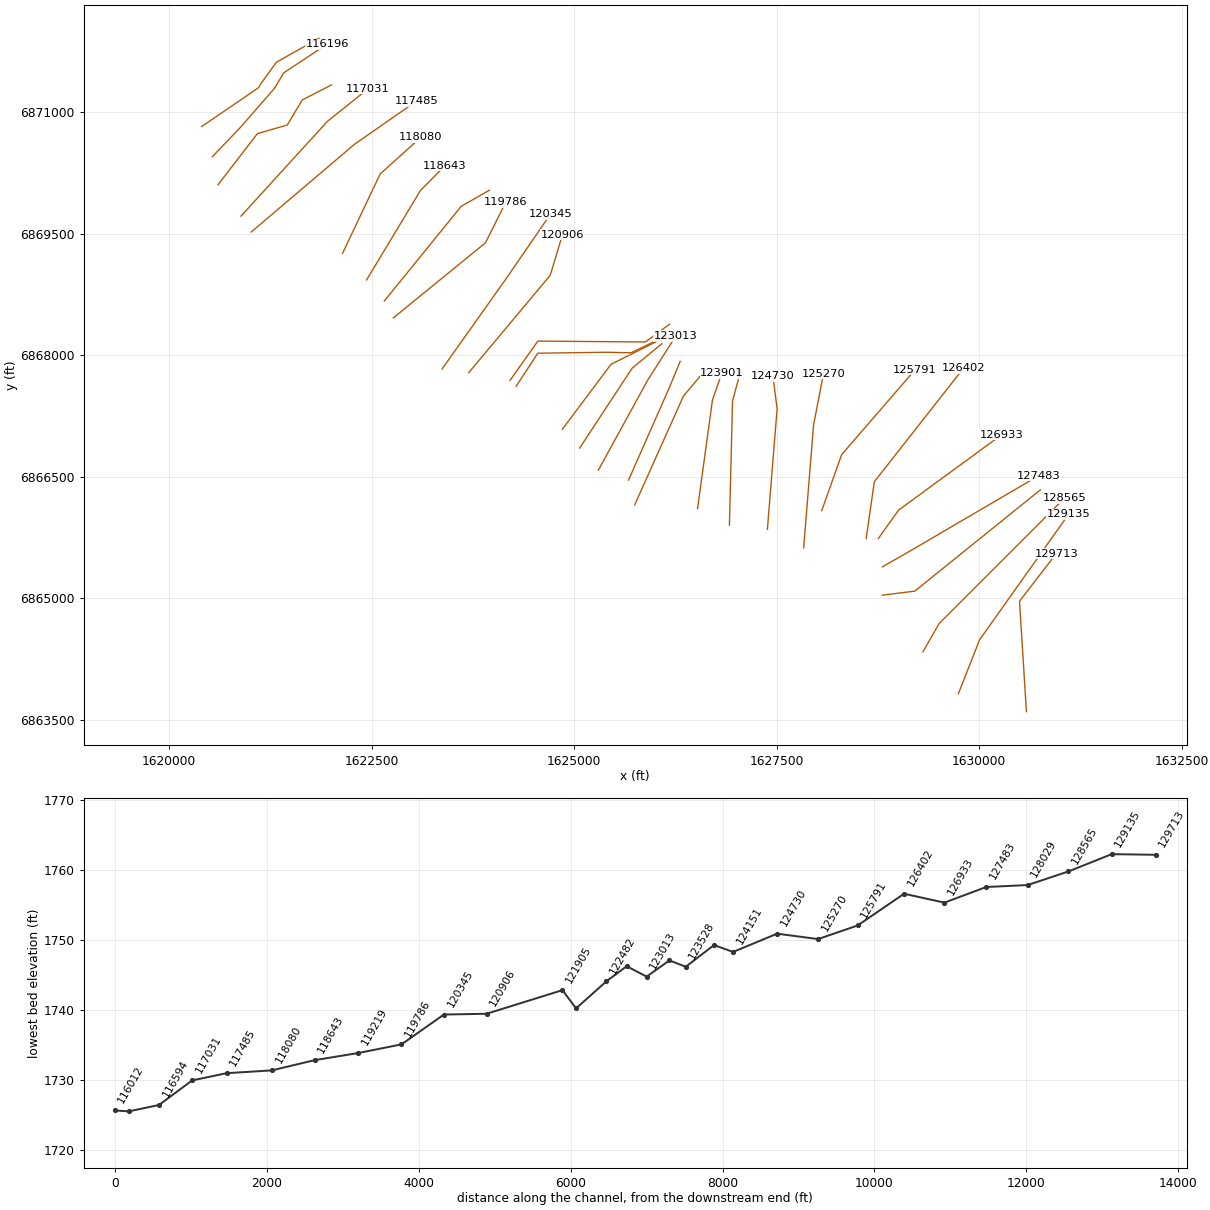
HEC-RAS study Deadman Creek.prj: Deadman Creek Base Level Engineering

--- Deadman Creek.g01 (geometry) --- (continued)

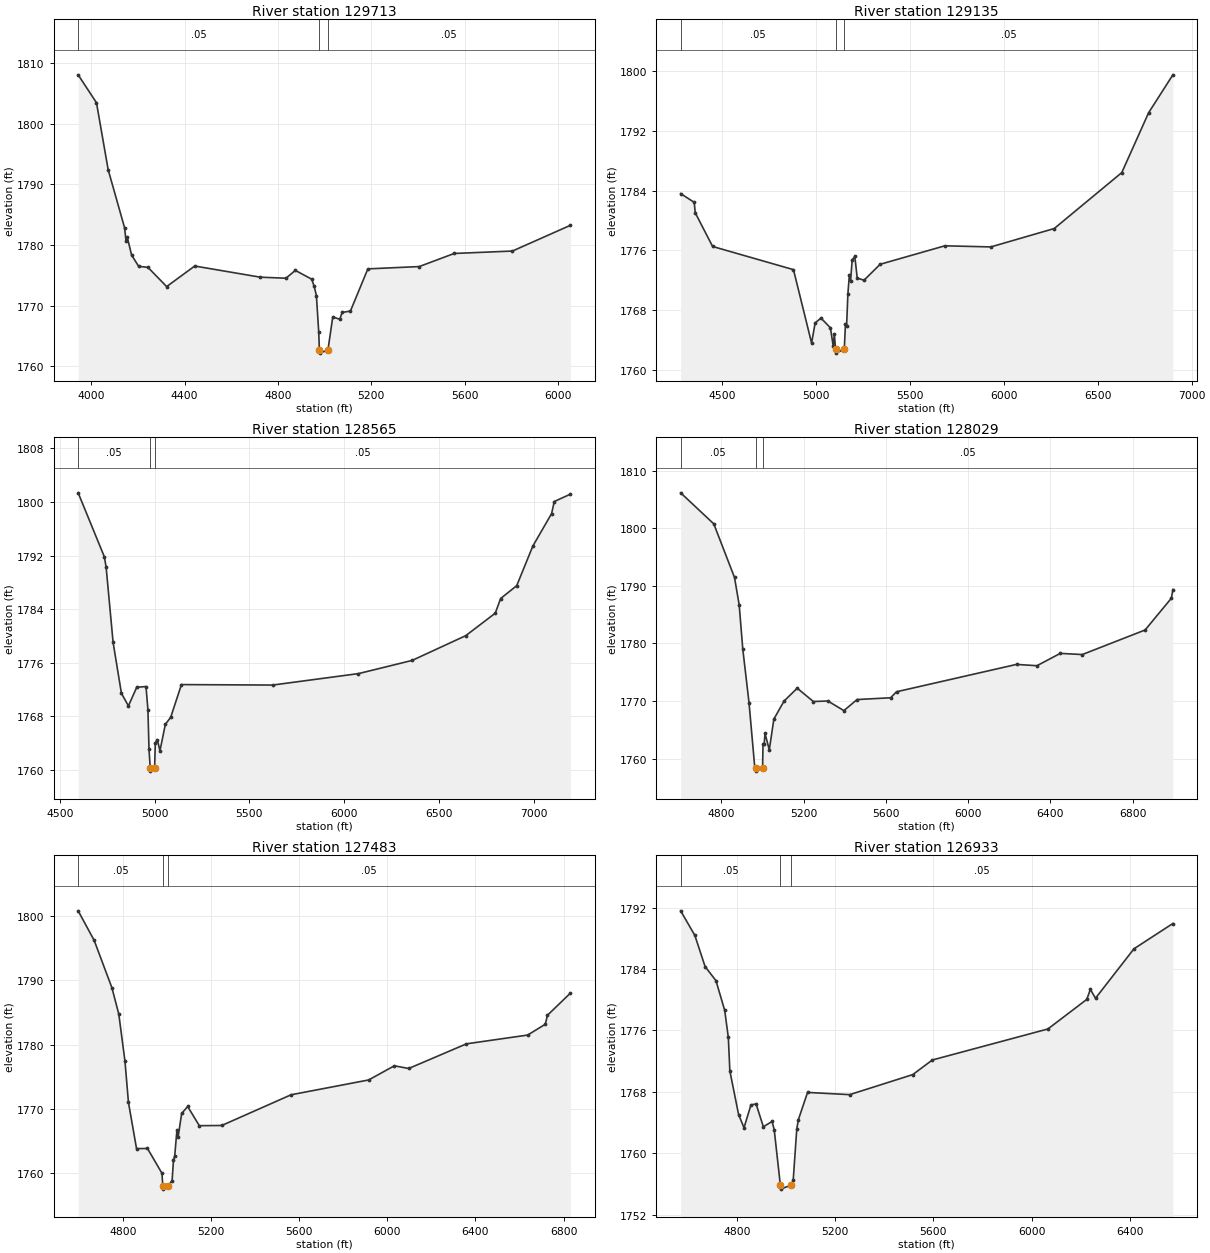
Type RM Length L Ch R = 1,129713,578,578,578
BEGIN DESCRIPTION:
Mapping XS e20c4c4d
END DESCRIPTION:
XS GIS Cut Line= 3
      1630582.90      6863599.64      1630497.55      6864962.91
      1630950.36      6865551.05
#Sta/Elev= 30
  3944.3 1808.05  4022.8 1803.45  4072.9 1792.40  4143.0 1782.86  4149.4 1780.65
  4154.4 1781.32  4173.1 1778.35  4203.2 1776.48  4243.2 1776.31  4323.4 1773.14
  4443.6 1776.53  4724.2 1774.69  4834.4 1774.52  4874.5 1775.81  4944.6 1774.36
  4955.3 1773.17  4964.7 1771.66  4974.7 1765.66  4977.5 1762.67  4978.3 1762.17
  5014.1 1762.67  5034.8 1768.14  5064.8 1767.75  5074.9 1768.88  5110.4 1769.10
  5185.1 1776.06  5405.0 1776.44  5555.1 1778.60  5804.3 1779.00  6052.5 1783.24
#Mann=3,-1,0
  3944.3    0.05       0  4977.5    0.03       0  5014.1    0.05       0
Bank Sta=4977.5,5014.1
Exp/Cntr=0.3,0.1

Type RM Length L Ch R = 1,129135,570,570,570
BEGIN DESCRIPTION:
Deadman Creek 155.0
END DESCRIPTION:
XS GIS Cut Line= 3
      1629742.02      6863819.81      1630005.00      6864488.00
      1631104.98      6866037.97
#Sta/Elev= 30
  4281.4 1783.59  4353.6 1782.42  4358.9 1781.03  4451.4 1776.52  4881.6 1773.42
  4978.0 1763.61  4996.8 1766.29  5027.8 1766.95  5078.2 1765.64  5093.0 1763.20
  5099.1 1764.83  5105.4 1762.76  5106.4 1762.26  5151.9 1762.76  5158.2 1766.16
  5164.3 1765.94  5171.1 1770.19  5179.1 1772.75  5185.2 1771.90  5193.9 1774.69
  5207.9 1775.20  5220.9 1772.29  5257.0 1772.01  5342.8 1774.14  5687.1 1776.61
  5931.4 1776.46  6269.0 1778.92  6628.3 1786.40  6771.0 1794.40  6900.1 1799.47
#Mann=3,-1,0
  4281.4    0.05       0  5105.4    0.03       0  5151.9    0.05       0
Bank Sta=5105.4,5151.9
Exp/Cntr=0.3,0.1

Type RM Length L Ch R = 1,128565,536,536,536
BEGIN DESCRIPTION:
Deadman Creek 154.0
END DESCRIPTION:
XS GIS Cut Line= 3
      1629304.98      6864337.96      1629505.00      6864688.00
      1631055.01      6866238.01
#Sta/Elev= 30
  4597.0 1801.37  4735.3 1791.80  4744.6 1790.24  4781.3 1779.01  4825.2 1771.41
  4862.0 1769.54  4905.9 1772.32  4954.8 1772.43  4964.9 1768.94  4970.6 1763.05
  4977.0 1760.29  4977.5 1759.79  5000.2 1760.29  5003.7 1763.97  5014.3 1764.49
  5028.4 1762.84  5056.7 1766.78  5085.0 1767.84  5141.6 1772.72  5622.4 1772.65
  6075.0 1774.36  6357.8 1776.33  6640.6 1780.03  6796.2 1783.39  6824.5 1785.58
  6909.3 1787.50  6994.2 1793.41  7093.2 1798.27  7107.3 1800.07  7192.2 1801.17
#Mann=3,-1,0
  4597.0    0.05       0  4977.0    0.05       0  5000.2    0.05       0
Bank Sta=4977,5000.2
Exp/Cntr=0.3,0.1

Type RM Length L Ch R = 1,128029,546,546,546
BEGIN DESCRIPTION:
Deadman Creek 153.0
END DESCRIPTION:
XS GIS Cut Line= 3
      1628805.03      6865038.00      1629205.00      6865088.00
      1630754.99      6866337.99
#Sta/Elev= 30
  4601.6 1806.14  4762.8 1800.75  4863.6 1791.45  4886.3 1786.68  4903.9 1779.00
  4934.1 1769.74  4961.8 1758.60  4967.5 1758.35  4968.2 1757.85  5000.1 1758.35
  5002.2 1762.56  5007.9 1762.56  5011.9 1764.39  5032.7 1761.55  5055.0 1766.88
  5104.6 1770.01  5168.6 1772.24  5247.0 1769.93  5317.4 1770.02  5395.7 1768.35
  5459.7 1770.27  5622.9 1770.58  5651.6 1771.62  6235.4 1776.37  6334.6 1776.14
  6448.1 1778.28  6555.3 1778.08  6860.8 1782.34  6988.7 1787.86  6995.9 1789.36
#Mann=3,-1,0
  4601.6    0.05       0  4967.5    0.03       0  5000.1    0.05       0
Bank Sta=4967.5,5000.1
Exp/Cntr=0.3,0.1

Type RM Length L Ch R = 1,127483,550,550,550
BEGIN DESCRIPTION:
Deadman Creek 152.0
END DESCRIPTION:
XS GIS Cut Line= 3
      1628805.00      6865388.00      1629155.00      6865588.00
      1630734.20      6866512.86
#Sta/Elev= 30
  4597.8 1800.78  4670.5 1796.19  4751.1 1788.82  4782.1 1784.76  4810.2 1777.44
  4826.0 1771.03  4862.7 1763.86  4912.4 1763.88  4977.9 1760.04  4982.0 1758.07
  4982.5 1757.57  5005.3 1758.07  5024.1 1758.90  5030.2 1762.03  5036.0 1762.75
  5045.9 1766.72  5051.7 1765.74  5067.4 1769.32  5094.7 1770.40  5147.5 1767.42
  5249.2 1767.45  5563.9 1772.22  5915.8 1774.52  6032.3 1776.72  6097.6 1776.30
  6359.5 1780.13  6637.1 1781.49  6717.2 1783.17  6727.1 1784.57  6831.0 1788.00
#Mann=3,-1,0
  4597.8    0.05       0  4982.0    0.05       0  5005.3    0.05       0
Bank Sta=4982,5005.3
Exp/Cntr=0.3,0.1

Type RM Length L Ch R = 1,126933,531,531,531
BEGIN DESCRIPTION:
Deadman Creek 151.0
END DESCRIPTION:
XS GIS Cut Line= 3
      1628754.97      6865737.96      1629005.00      6866088.00
      1630275.86      6867018.06
#Sta/Elev= 30
  4570.6 1791.57  4628.4 1788.37  4670.2 1784.31  4714.4 1782.48  4750.1 1778.60
  4764.8 1775.08  4771.0 1770.73  4806.6 1765.05  4828.7 1763.33  4857.0 1766.31
  4877.9 1766.43  4907.4 1763.46  4943.0 1764.15  4951.6 1763.10  4976.8 1755.84
  4977.7 1755.34  5019.0 1755.84  5029.0 1756.48  5043.6 1763.19  5050.3 1764.40
  5087.5 1767.93  5259.0 1767.64  5516.1 1770.25  5595.6 1772.15  6066.5 1776.19
  6224.9 1780.04  6239.5 1781.34  6260.4 1780.19  6417.1 1786.63  6575.6 1789.92
#Mann=3,-1,0
  4570.6    0.05       0  4976.8    0.03       0  5019.0    0.05       0
Bank Sta=4976.8,5019
Exp/Cntr=0.3,0.1

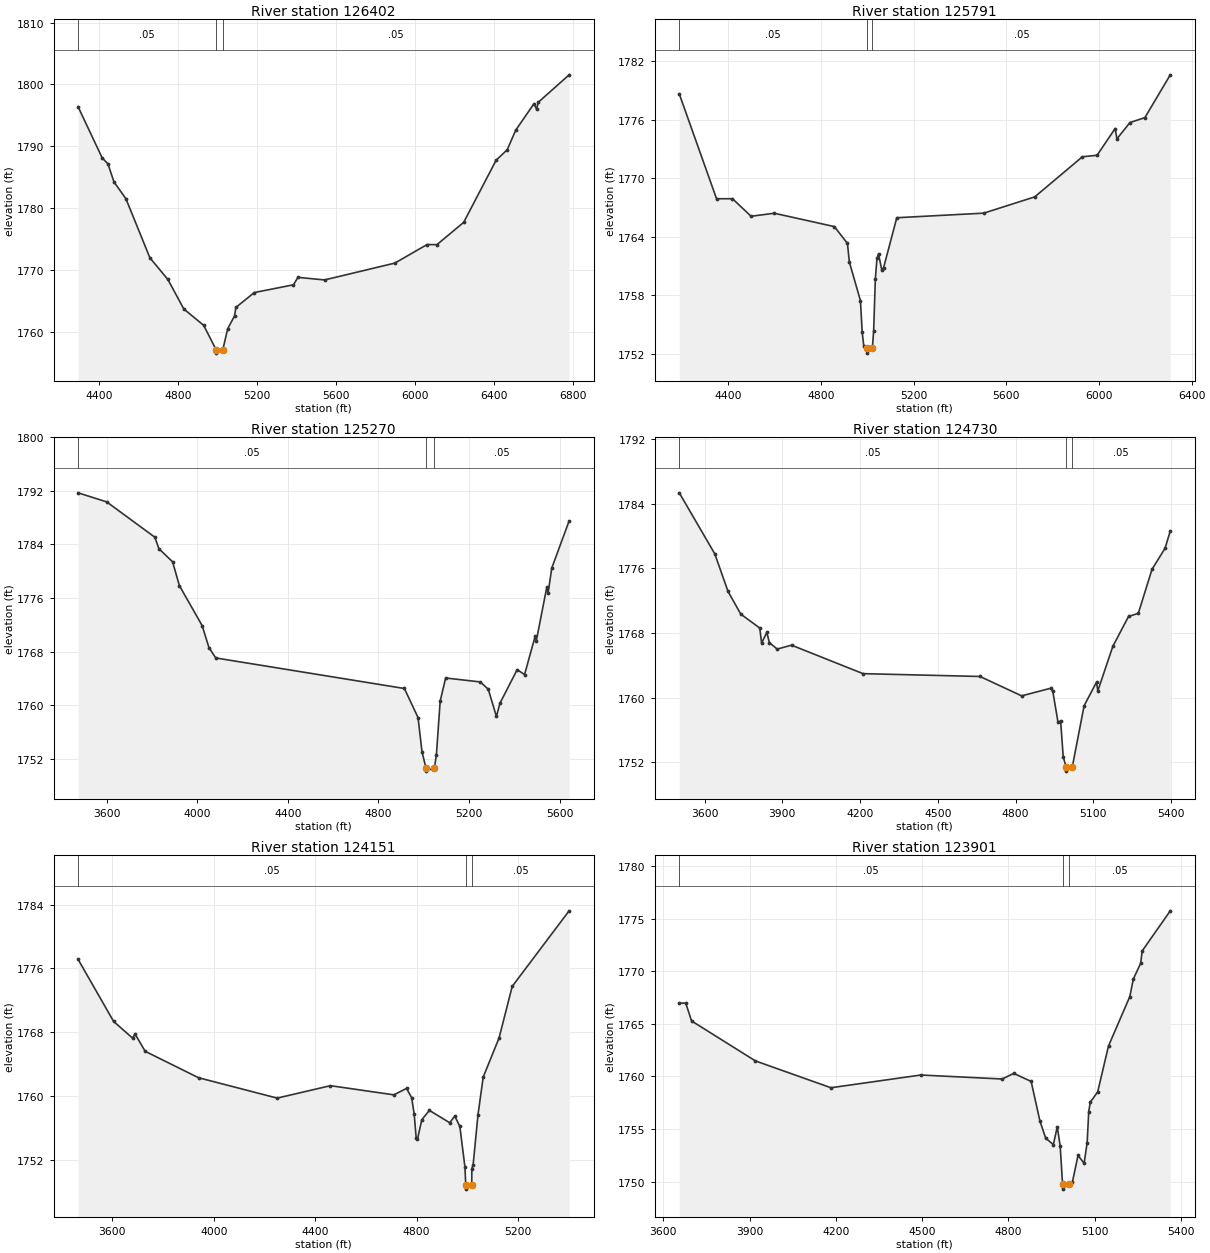
Type RM Length L Ch R = 1,126402,611,611,611
BEGIN DESCRIPTION:
Deadman Creek 150.0
END DESCRIPTION:
XS GIS Cut Line= 3
      1628605.00      6865738.00      1628705.00      6866438.00
      1629805.03      6867838.04
#Sta/Elev= 30
  4293.7 1796.40  4414.9 1788.20  4445.2 1787.15  4475.5 1784.26  4536.1 1781.54
  4657.4 1772.01  4748.3 1768.52  4829.1 1763.75  4930.1 1761.09  4993.6 1757.11
  4994.3 1756.61  5026.5 1757.11  5051.4 1760.53  5086.6 1762.64  5093.0 1763.99
  5186.1 1766.39  5384.9 1767.65  5407.5 1768.85  5542.2 1768.43  5898.3 1771.15
  6061.8 1774.15  6111.6 1774.13  6247.1 1777.73  6411.6 1787.77  6467.7 1789.46
  6511.0 1792.63  6603.2 1796.89  6616.8 1796.00  6624.9 1797.12  6781.3 1801.56
#Mann=3,-1,0
  4293.7    0.05       0  4993.6    0.03       0  5026.5    0.05       0
Bank Sta=4993.6,5026.5
Exp/Cntr=0.3,0.1

Type RM Length L Ch R = 1,125791,521,521,521
BEGIN DESCRIPTION:
Deadman Creek 149.0
END DESCRIPTION:
XS GIS Cut Line= 3
      1628056.03      6866081.71      1628301.90      6866773.27
      1629208.14      6867820.14
#Sta/Elev= 30
  4189.2 1778.67  4350.0 1767.92  4418.8 1767.92  4499.0 1766.12  4599.2 1766.43
  4858.5 1765.06  4914.9 1763.33  4923.0 1761.43  4970.9 1757.46  4978.5 1754.20
  4985.2 1752.84  4998.9 1752.58  4999.4 1752.08  5022.4 1752.58  5027.9 1754.38
  5035.2 1759.69  5042.2 1761.81  5048.8 1762.26  5063.0 1760.61  5070.7 1760.84
  5127.7 1765.97  5502.8 1766.44  5723.0 1768.11  5928.3 1772.22  5992.0 1772.38
  6069.8 1775.12  6077.5 1774.06  6133.5 1775.73  6198.1 1776.24  6307.8 1780.63
#Mann=3,-1,0
  4189.2    0.05       0  4998.9    0.03       0  5022.4    0.05       0
Bank Sta=4998.9,5022.4
Exp/Cntr=0.3,0.1

Type RM Length L Ch R = 1,125270,540,540,540
BEGIN DESCRIPTION:
Deadman Creek 148.0
END DESCRIPTION:
XS GIS Cut Line= 3
      1627833.15      6865622.27      1627955.00      6867138.00
      1628077.91      6867773.09
#Sta/Elev= 30
  3474.1 1791.70  3600.2 1790.35  3812.6 1785.08  3831.0 1783.35  3891.2 1781.40
  3921.3 1777.84  4021.6 1771.88  4051.7 1768.60  4081.8 1767.04  4914.5 1762.48
  4974.7 1758.14  4992.2 1753.03  5009.6 1750.64  5010.4 1750.14  5047.2 1750.64
  5055.8 1752.59  5072.4 1760.59  5096.6 1764.05  5249.4 1763.46  5284.6 1762.38
  5320.7 1758.31  5336.4 1760.29  5412.3 1765.29  5445.0 1764.56  5491.7 1770.29
  5496.8 1769.60  5543.5 1777.68  5548.6 1776.68  5565.1 1780.47  5641.6 1787.50
#Mann=3,-1,0
  3474.1    0.05       0  5009.6    0.03       0  5047.2    0.05       0
Bank Sta=5009.6,5047.2
Exp/Cntr=0.3,0.1

Type RM Length L Ch R = 1,124730,579,579,579
BEGIN DESCRIPTION:
Deadman Creek 147.0
END DESCRIPTION:
XS GIS Cut Line= 3
      1627385.23      6865851.38      1627505.00      6867338.00
      1627455.01      6867737.95
#Sta/Elev= 30
  3502.6 1785.37  3639.7 1777.81  3690.7 1773.16  3740.0 1770.35  3813.1 1768.63
  3820.2 1766.77  3840.3 1768.08  3850.3 1766.83  3880.4 1766.02  3935.6 1766.51
  4211.5 1762.98  4663.0 1762.63  4823.5 1760.23  4935.3 1761.17  4943.9 1760.77
  4963.9 1756.96  4974.0 1757.12  4984.0 1752.69  4995.3 1751.41  4995.8 1750.91
  5018.9 1751.41  5064.6 1759.01  5112.4 1761.92  5117.5 1760.85  5175.4 1766.36
  5235.9 1770.06  5273.7 1770.45  5326.6 1775.90  5377.0 1778.51  5397.1 1780.66
#Mann=3,-1,0
  3502.6    0.05       0  4995.3    0.05       0  5018.9    0.05       0
Bank Sta=4995.3,5018.9
Exp/Cntr=0.3,0.1

Type RM Length L Ch R = 1,124151,250,250,250
BEGIN DESCRIPTION:
Deadman Creek 146.0
END DESCRIPTION:
XS GIS Cut Line= 3
      1626916.48      6865903.49      1626955.00      6867438.00
      1627061.99      6867824.17
#Sta/Elev= 30
  3465.2 1777.13  3605.1 1769.35  3679.8 1767.25  3689.8 1767.76  3729.8 1765.59
  3939.9 1762.28  4250.0 1759.72  4460.0 1761.28  4710.1 1760.13  4760.1 1760.94
  4780.1 1759.77  4790.1 1757.75  4798.0 1754.72  4803.0 1754.53  4820.1 1757.01
  4850.1 1758.18  4930.2 1756.63  4950.2 1757.47  4970.2 1756.16  4990.2 1751.08
  4993.5 1748.80  4994.0 1748.30  5017.1 1748.80  5017.3 1750.85  5022.5 1751.35
  5041.7 1757.64  5062.4 1762.37  5124.7 1767.26  5176.6 1773.74  5400.9 1783.22
#Mann=3,-1,0
  3465.2    0.05       0  4993.5    0.05       0  5017.1    0.05       0
Bank Sta=4993.5,5017.1
Exp/Cntr=0.3,0.1

Type RM Length L Ch R = 1,123901,373,373,373
BEGIN DESCRIPTION:
Mapping XS c9b0c5d8
END DESCRIPTION:
XS GIS Cut Line= 3
      1626523.07      6866105.62      1626707.19      6867448.39
      1626823.96      6867780.73
#Sta/Elev= 30
  3655.5 1766.99  3678.1 1766.97  3698.3 1765.28  3920.3 1761.48  4182.8 1758.93
  4495.7 1760.14  4778.3 1759.76  4818.7 1760.29  4879.2 1759.53  4909.5 1755.79
  4929.7 1754.14  4956.4 1753.52  4970.1 1755.22  4980.2 1753.38  4988.4 1749.79
  4988.9 1749.29  5012.0 1749.79  5022.8 1749.98  5042.2 1752.49  5063.4 1751.75
  5074.0 1753.72  5079.5 1756.67  5084.8 1757.55  5110.5 1758.53  5148.2 1762.90
  5222.4 1767.60  5234.4 1769.25  5260.1 1770.77  5265.4 1771.94  5363.1 1775.75
#Mann=3,-1,0
  3655.5    0.05       0  4988.4    0.05       0  5012.0    0.05       0
Bank Sta=4988.4,5012
Exp/Cntr=0.3,0.1

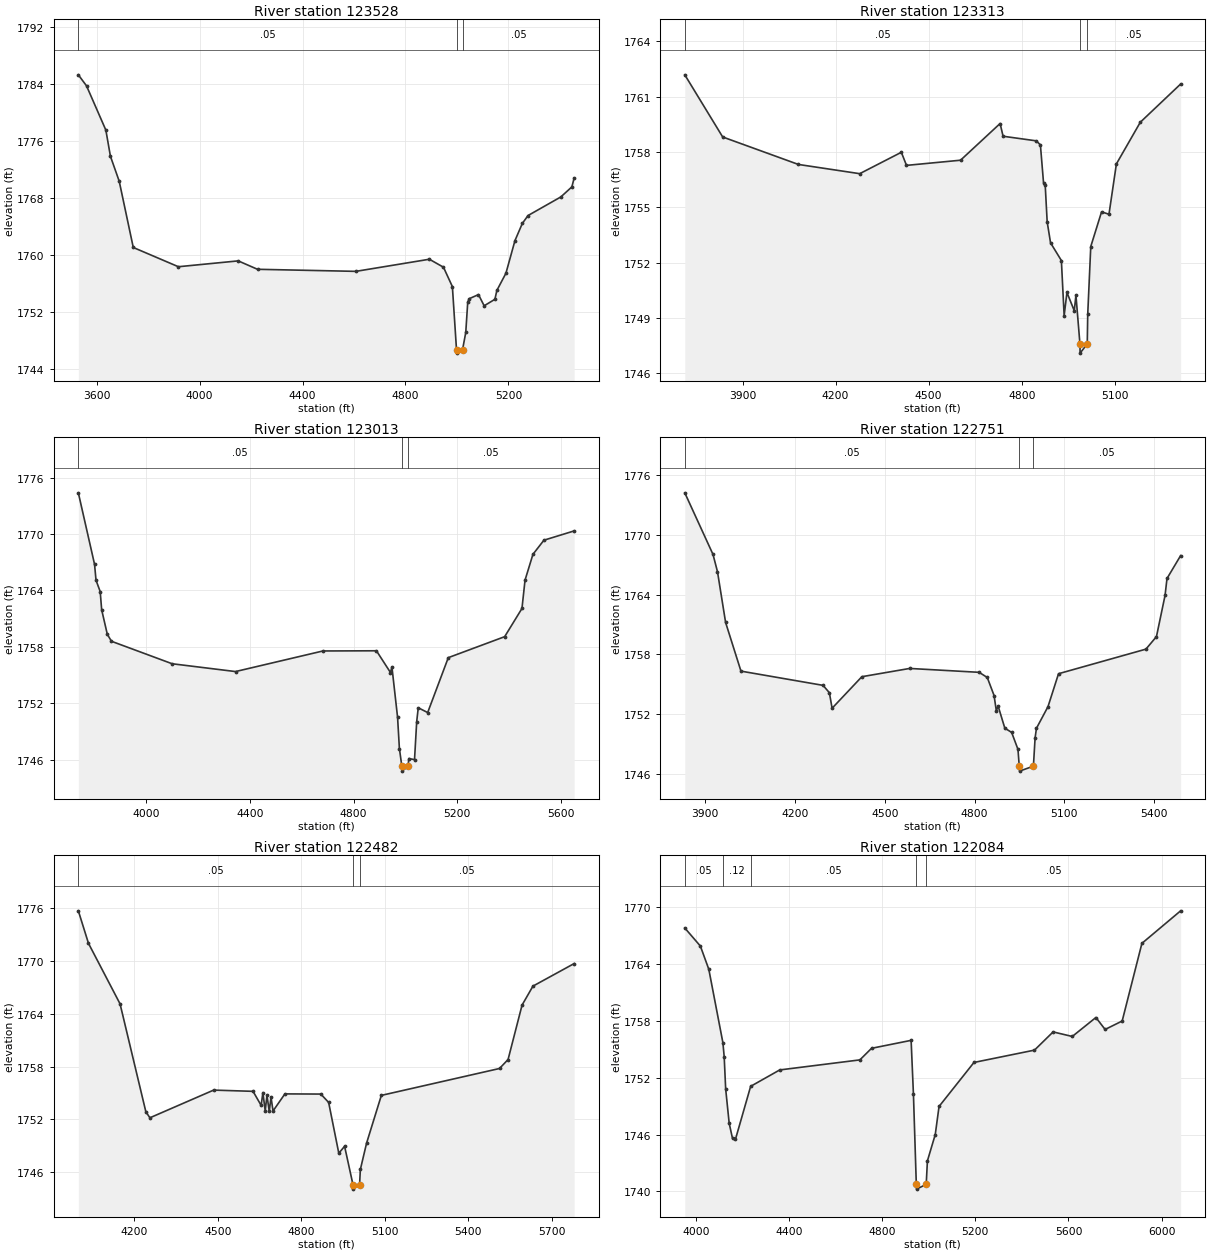
Type RM Length L Ch R = 1,123528,215,215,215
BEGIN DESCRIPTION:
Deadman Creek 145.0
END DESCRIPTION:
XS GIS Cut Line= 3
      1625747.24      6866153.17      1626348.83      6867495.86
      1626641.87      6867844.45
#Sta/Elev= 30
  3528.7 1785.23  3560.6 1783.68  3635.7 1777.47  3653.4 1773.81  3687.5 1770.31
  3742.2 1761.01  3917.5 1758.31  4150.0 1759.13  4225.0 1757.95  4607.0 1757.66
  4892.8 1759.36  4947.6 1758.24  4982.2 1755.52  4998.2 1746.69  4998.7 1746.19
  5021.8 1746.69  5034.2 1749.09  5041.9 1753.37  5048.5 1753.84  5083.6 1754.40
  5105.7 1752.83  5147.4 1753.74  5155.1 1754.99  5190.3 1757.40  5225.4 1761.98
  5254.0 1764.38  5276.1 1765.49  5403.6 1768.10  5446.5 1769.51  5455.4 1770.76
#Mann=3,-1,0
  3528.7    0.05       0  4998.2    0.03       0  5021.8    0.05       0
Bank Sta=4998.2,5021.8
Exp/Cntr=0.3,0.1

Type RM Length L Ch R = 1,123313,300,300,300
BEGIN DESCRIPTION:
Mapping XS 7e7b5932
END DESCRIPTION:
XS GIS Cut Line= 3
      1625671.58      6866459.41      1626175.06      6867600.93
      1626308.90      6867924.74
#Sta/Elev= 30
  3714.0 1762.18  3836.1 1758.81  4080.2 1757.32  4277.7 1756.82  4411.9 1757.98
  4428.5 1757.27  4602.7 1757.55  4730.2 1759.54  4739.8 1758.85  4846.8 1758.60
  4860.1 1758.38  4870.1 1756.34  4875.6 1756.19  4881.9 1754.21  4892.8 1753.07
  4927.7 1752.11  4936.6 1749.12  4945.6 1750.38  4969.2 1749.39  4974.6 1750.23
  4987.5 1747.59  4988.0 1747.09  5011.1 1747.59  5012.6 1749.19  5022.4 1752.87
  5057.2 1754.75  5081.1 1754.62  5105.0 1757.35  5182.1 1759.61  5312.0 1761.68
#Mann=3,-1,0
  3714.0    0.05       0  4987.5    0.05       0  5011.1    0.05       0
Bank Sta=4987.5,5011.1
Exp/Cntr=0.3,0.1

Type RM Length L Ch R = 1,123013,262,262,262
BEGIN DESCRIPTION:
Deadman Creek 144.0
END DESCRIPTION:
XS GIS Cut Line= 3
      1625298.35      6866581.01      1625905.00      6867688.00
      1626254.98      6868237.97
#Sta/Elev= 30
  3737.6 1774.38  3800.2 1766.78  3805.9 1765.08  3822.0 1763.88  3827.7 1761.94
  3849.5 1759.33  3865.6 1758.59  4099.8 1756.20  4344.4 1755.37  4681.9 1757.56
  4888.5 1757.58  4942.6 1755.27  4948.3 1755.85  4970.1 1750.50  4977.1 1747.18
  4986.7 1745.28  4987.2 1744.78  5010.4 1745.28  5013.5 1746.12  5035.5 1746.00
  5043.9 1750.04  5049.9 1751.52  5086.3 1751.01  5165.9 1756.85  5383.5 1759.08
  5450.3 1762.08  5462.2 1765.10  5492.7 1767.84  5535.0 1769.34  5651.8 1770.33
#Mann=3,-1,0
  3737.6    0.05       0  4986.7    0.05       0  5010.4    0.05       0
Bank Sta=4986.7,5010.4
Exp/Cntr=0.3,0.1

Type RM Length L Ch R = 1,122751,269,269,269
BEGIN DESCRIPTION:
Mapping XS fe411f91
END DESCRIPTION:
XS GIS Cut Line= 3
      1625068.27      6866854.38      1625715.00      6867839.65
      1626083.62      6868143.22
#Sta/Elev= 30
  3832.1 1774.24  3926.3 1768.05  3941.3 1766.31  3968.4 1761.21  4019.7 1756.32
  4293.9 1754.89  4315.0 1754.15  4324.1 1752.59  4423.5 1755.76  4583.2 1756.59
  4815.3 1756.20  4842.4 1755.68  4865.1 1753.87  4872.6 1752.33  4878.5 1752.82
  4901.0 1750.59  4923.8 1750.16  4944.9 1748.46  4949.2 1746.77  4950.2 1746.27
  4996.5 1746.77  5002.1 1749.60  5006.7 1750.58  5045.2 1752.75  5080.4 1756.06
  5372.3 1758.53  5407.5 1759.79  5436.2 1763.93  5442.7 1765.63  5488.2 1767.93
#Mann=3,-1,0
  3832.1    0.05       0  4949.2    0.05       0  4996.5    0.05       0
Bank Sta=4949.2,4996.5
Exp/Cntr=0.3,0.1

Type RM Length L Ch R = 1,122482,398,398,398
BEGIN DESCRIPTION:
Deadman Creek 143.0
END DESCRIPTION:
XS GIS Cut Line= 3
      1624854.98      6867087.97      1625455.00      6867888.00
      1626155.04      6868238.02
#Sta/Elev= 30
  3998.3 1775.66  4034.8 1771.97  4148.3 1765.11  4241.0 1752.88  4255.6 1752.19
  4484.8 1755.33  4626.5 1755.19  4655.6 1753.59  4661.9 1755.05  4670.2 1752.97
  4676.5 1754.74  4684.8 1752.91  4691.0 1754.55  4698.3 1752.96  4741.0 1754.90
  4870.2 1754.88  4898.3 1753.93  4934.8 1748.17  4955.6 1748.96  4985.8 1744.60
  4986.3 1744.10  5009.5 1744.60  5012.3 1746.33  5034.7 1749.32  5087.8 1754.73
  5512.6 1757.78  5543.4 1758.80  5593.7 1764.97  5632.8 1767.12  5781.0 1769.68
#Mann=3,-1,0
  3998.3    0.05       0  4985.8    0.05       0  5009.5    0.05       0
Bank Sta=4985.8,5009.5
Exp/Cntr=0.3,0.1

Type RM Length L Ch R = 1,122084,179,179,179
BEGIN DESCRIPTION:
Mapping XS cff60a4b
END DESCRIPTION:
XS GIS Cut Line= 5
      1624283.55      6867616.49      1624551.07      6868024.97
      1625391.01      6868036.47      1625704.55      6868030.72
      1626144.04      6868243.29
#Sta/Elev= 30
  3951.7 1767.78  4018.7 1765.87  4054.9 1763.42  4115.4 1755.68  4120.9 1754.21
  4127.3 1750.80  4142.4 1747.18  4156.7 1745.58  4169.5 1745.51  4234.6 1751.08
  4359.5 1752.81  4703.9 1753.87  4753.9 1755.09  4924.0 1755.93  4934.0 1750.22
  4946.3 1740.74  4947.2 1740.24  4988.8 1740.74  4994.0 1743.22  5027.7 1746.00
  5044.0 1748.96  5194.0 1753.60  5454.0 1754.90  5534.0 1756.82  5616.3 1756.34
  5717.8 1758.34  5757.4 1757.08  5830.7 1757.97  5915.5 1766.16  6081.8 1769.59
#Mann=5,-1,0
  3951.7    0.05       0  4115.4    0.12       0  4234.6    0.05       0
  4946.3    0.05       0  4988.8    0.05       0
Bank Sta=4946.3,4988.8
Exp/Cntr=0.3,0.1

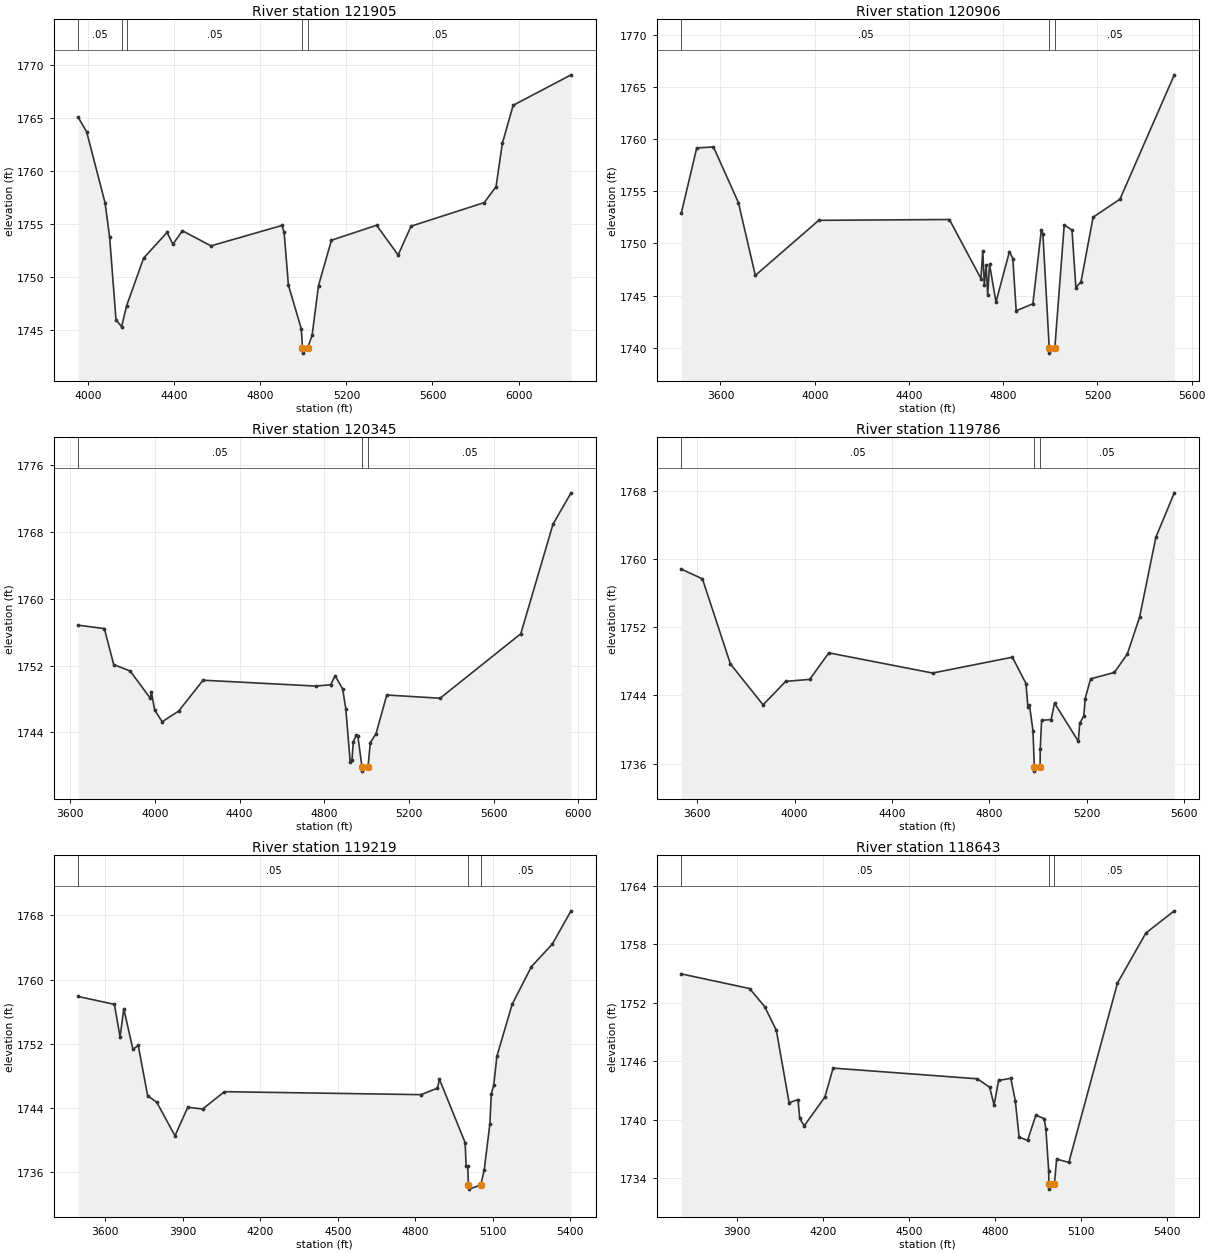
Type RM Length L Ch R = 1,121905,999,999,999
BEGIN DESCRIPTION:
Mapping XS 6e8a3132
END DESCRIPTION:
XS GIS Cut Line= 4
      1624208.12      6867689.90      1624551.90      6868174.31
      1625880.02      6868163.89      1626176.87      6868382.62
#Sta/Elev= 30
  3953.3 1765.03  3992.5 1763.68  4078.6 1756.95  4099.5 1753.74  4129.1 1745.99
  4154.9 1745.34  4178.7 1747.32  4257.5 1751.79  4366.5 1754.21  4393.5 1753.09
  4437.8 1754.36  4570.4 1752.94  4900.4 1754.86  4910.4 1754.24  4930.4 1749.25
  4990.4 1745.13  4995.9 1743.35  4996.4 1742.85  5019.6 1743.35  5040.4 1744.51
  5070.4 1749.21  5130.4 1753.47  5340.4 1754.88  5440.4 1752.08  5500.4 1754.79
  5840.4 1757.01  5895.6 1758.51  5924.8 1762.58  5975.0 1766.16  6244.2 1769.03
#Mann=5,-1,0
  3953.3    0.05       0  4154.9    0.12       0  4178.7    0.05       0
  4995.9    0.03       0  5019.6    0.05       0
Bank Sta=4995.9,5019.6
Exp/Cntr=0.3,0.1

Type RM Length L Ch R = 1,120906,561,561,561
BEGIN DESCRIPTION:
Deadman Creek 141.0
END DESCRIPTION:
XS GIS Cut Line= 3
      1623697.72      6867783.67      1624705.00      6868988.00
      1624855.01      6869488.04
#Sta/Elev= 30
  3434.2 1752.95  3499.3 1759.15  3570.2 1759.25  3676.3 1753.90  3747.9 1746.93
  4017.2 1752.21  4571.6 1752.29  4705.6 1746.63  4713.4 1749.30  4719.9 1746.00
  4727.7 1747.95  4734.2 1745.04  4742.0 1748.00  4769.6 1744.37  4826.6 1749.22
  4840.9 1748.55  4855.2 1743.54  4926.0 1744.21  4961.9 1751.27  4968.5 1750.91
  4995.5 1739.98  4996.0 1739.48  5019.2 1739.98  5059.1 1751.77  5092.1 1751.28
  5108.6 1745.77  5130.4 1746.33  5181.7 1752.51  5295.7 1754.24  5526.3 1766.16
#Mann=3,-1,0
  3434.2    0.05       0  4995.5    0.03       0  5019.2    0.05       0
Bank Sta=4995.5,5019.2
Exp/Cntr=0.3,0.1

Type RM Length L Ch R = 1,120345,559,559,559
BEGIN DESCRIPTION:
Deadman Creek 140.0
END DESCRIPTION:
XS GIS Cut Line= 3
      1623369.61      6867830.57      1624155.00      6868938.00
      1624705.01      6869738.02
#Sta/Elev= 30
  3637.9 1756.83  3761.5 1756.43  3805.8 1752.12  3883.3 1751.35  3978.0 1748.12
  3984.2 1748.79  3999.0 1746.69  4034.7 1745.28  4112.9 1746.56  4227.8 1750.25
  4759.3 1749.55  4830.7 1749.70  4851.6 1750.79  4887.3 1749.20  4902.0 1746.86
  4922.9 1740.48  4931.6 1740.75  4937.7 1742.90  4952.5 1743.72  4958.8 1743.61
  4978.7 1739.87  4979.3 1739.37  5007.1 1739.87  5017.9 1742.78  5044.9 1743.84
  5095.7 1748.48  5347.5 1748.09  5728.9 1755.81  5881.2 1768.93  5966.4 1772.67
#Mann=3,-1,0
  3637.9    0.05       0  4978.7    0.03       0  5007.1    0.05       0
Bank Sta=4978.7,5007.1
Exp/Cntr=0.3,0.1

Type RM Length L Ch R = 1,119786,567,567,567
BEGIN DESCRIPTION:
Deadman Creek 139.0
END DESCRIPTION:
XS GIS Cut Line= 3
      1622768.66      6868462.03      1623905.00      6869388.00
      1624155.02      6869888.04
#Sta/Elev= 30
  3535.4 1758.79  3621.8 1757.65  3736.7 1747.68  3870.9 1742.88  3963.6 1745.63
  4062.7 1745.87  4141.0 1748.98  4567.5 1746.61  4895.0 1748.47  4951.0 1745.38
  4958.9 1742.61  4965.3 1742.86  4979.7 1739.86  4985.2 1735.61  4985.7 1735.11
  5008.9 1735.61  5009.6 1737.70  5015.2 1741.06  5054.4 1741.16  5068.3 1743.08
  5166.2 1738.60  5171.7 1740.73  5188.5 1741.56  5194.1 1743.60  5216.5 1745.93
  5314.3 1746.68  5367.4 1748.85  5417.7 1753.16  5484.8 1762.54  5560.3 1767.74
#Mann=3,-1,0
  3535.4    0.05       0  4985.2    0.05       0  5008.9    0.05       0
Bank Sta=4985.2,5008.9
Exp/Cntr=0.3,0.1

Type RM Length L Ch R = 1,119219,576,576,576
BEGIN DESCRIPTION:
Deadman Creek 138.0
END DESCRIPTION:
XS GIS Cut Line= 3
      1622656.09      6868669.13      1623605.00      6869838.00
      1623955.03      6870038.02
#Sta/Elev= 30
  3494.7 1757.90  3634.9 1756.92  3656.9 1752.86  3671.3 1756.37  3706.5 1751.32
  3727.3 1751.79  3763.7 1745.53  3799.1 1744.71  3869.5 1740.53  3919.1 1744.09
  3976.6 1743.87  4061.3 1746.03  4822.1 1745.66  4886.0 1746.47  4893.9 1747.56
  4993.1 1739.68  4997.0 1736.78  5003.1 1736.78  5006.0 1734.38  5007.0 1733.88
  5053.5 1734.38  5067.2 1736.29  5088.8 1741.97  5094.6 1745.77  5103.9 1746.83
  5116.1 1750.44  5175.2 1756.92  5250.0 1761.63  5330.7 1764.43  5403.4 1768.58
#Mann=3,-1,0
  3494.7    0.05       0  5006.0    0.05       0  5053.5    0.05       0
Bank Sta=5006,5053.5
Exp/Cntr=0.3,0.1

Type RM Length L Ch R = 1,118643,563,563,563
BEGIN DESCRIPTION:
Deadman Creek 137.0
END DESCRIPTION:
XS GIS Cut Line= 3
      1622437.32      6868929.53      1623105.00      6870038.00
      1623405.01      6870338.01
#Sta/Elev= 30
  3706.4 1754.96  3944.0 1753.46  3996.5 1751.61  4037.3 1749.18  4081.9 1741.73
  4113.0 1742.06  4118.8 1740.12  4134.3 1739.35  4206.6 1742.32  4235.3 1745.29
  4738.3 1744.19  4781.0 1743.32  4796.5 1741.50  4812.1 1744.02  4854.8 1744.24
  4870.3 1741.96  4883.7 1738.21  4913.0 1737.86  4942.1 1740.46  4971.3 1740.10
  4977.1 1739.01  4986.8 1734.77  4987.6 1733.36  4988.0 1732.86  5006.6 1733.36
  5014.6 1735.95  5057.0 1735.60  5226.7 1754.03  5325.7 1759.16  5424.7 1761.44
#Mann=3,-1,0
  3706.4    0.05       0  4987.6    0.05       0  5006.6    0.05       0
Bank Sta=4987.6,5006.6
Exp/Cntr=0.3,0.1

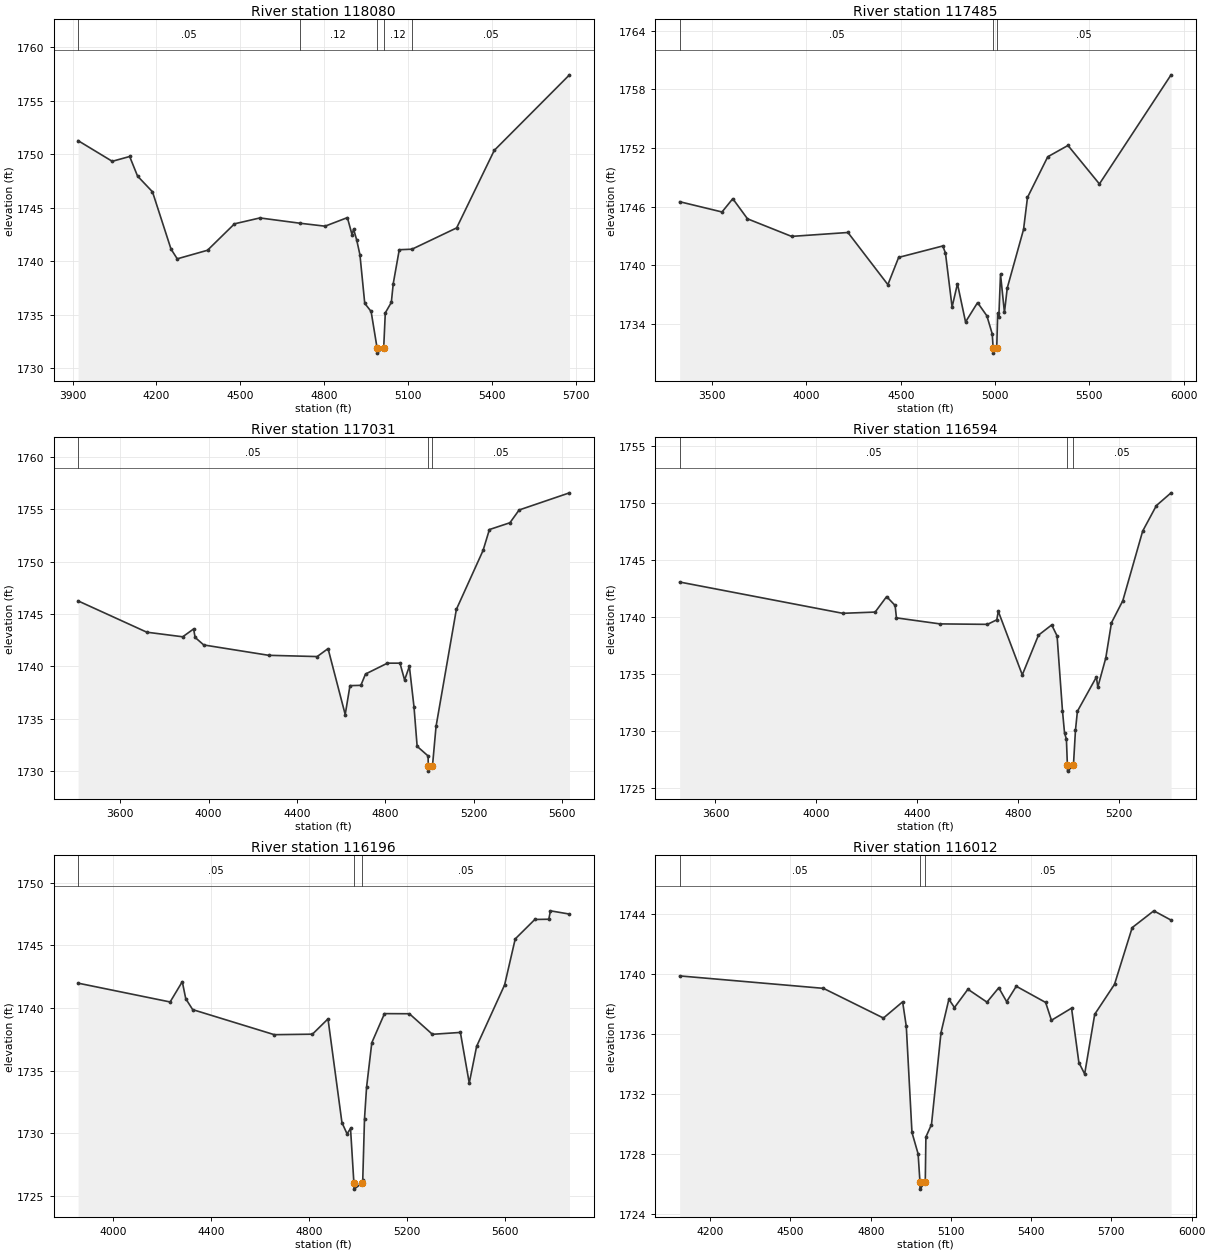
Type RM Length L Ch R = 1,118080,595,595,595
BEGIN DESCRIPTION:
Deadman Creek 136.0
END DESCRIPTION:
XS GIS Cut Line= 3
      1622140.45      6869257.67      1622605.00      6870238.00
      1623104.99      6870687.99
#Sta/Elev= 30
  3919.9 1751.25  4042.0 1749.32  4104.3 1749.77  4132.5 1747.94  4185.9 1746.47
  4252.2 1741.12  4274.5 1740.21  4382.7 1741.01  4479.2 1743.48  4570.2 1744.03
  4712.1 1743.54  4803.1 1743.26  4883.0 1744.06  4899.6 1742.47  4905.2 1742.98
  4916.2 1741.98  4927.9 1740.59  4945.1 1736.05  4967.9 1735.29  4989.1 1731.90
  4989.6 1731.40  5012.9 1731.90  5018.6 1735.16  5040.2 1736.14  5047.0 1737.89
  5068.6 1741.06  5114.1 1741.11  5273.8 1743.10  5408.3 1750.34  5677.4 1757.40
#Mann=5,-1,0
  3919.9    0.05       0  4712.1    0.12       0  4989.1    0.07       0
  5012.9    0.12       0  5114.1    0.05       0
Bank Sta=4989.1,5012.9
Exp/Cntr=0.3,0.1

Type RM Length L Ch R = 1,117485,454,454,454
BEGIN DESCRIPTION:
Deadman Creek 135.0
END DESCRIPTION:
XS GIS Cut Line= 4
      1621014.32      6869521.55      1621426.90      6869872.22
      1622288.70      6870604.70      1623054.99      6871138.00
#Sta/Elev= 30
  3327.5 1746.50  3552.0 1745.45  3609.1 1746.81  3687.1 1744.75  3921.0 1742.95
  4219.8 1743.35  4431.7 1738.01  4488.8 1740.80  4722.8 1741.97  4737.0 1741.25
  4772.2 1735.72  4800.7 1738.10  4843.6 1734.19  4907.3 1736.17  4956.7 1734.82
  4985.3 1732.96  4989.9 1731.50  4990.3 1731.00  5009.0 1731.50  5014.1 1735.11
  5020.2 1734.74  5029.0 1739.08  5049.9 1735.16  5064.8 1737.67  5151.2 1743.66
  5172.1 1746.94  5279.5 1751.10  5386.8 1752.26  5553.5 1748.32  5933.6 1759.49
#Mann=3,-1,0
  3327.5    0.05       0  4989.9    0.03       0  5009.0    0.05       0
Bank Sta=4989.9,5009
Exp/Cntr=0.3,0.1

Type RM Length L Ch R = 1,117031,437,437,437
BEGIN DESCRIPTION:
Deadman Creek 134.0
END DESCRIPTION:
XS GIS Cut Line= 4
      1620886.90      6869717.20      1621270.65      6870137.85
      1621955.00      6870888.00      1622454.98      6871287.99
#Sta/Elev= 30
  3409.4 1746.24  3720.3 1743.25  3883.1 1742.81  3932.5 1743.56  3939.2 1742.75
  3978.3 1742.03  4272.3 1741.04  4491.9 1740.92  4541.2 1741.68  4618.9 1735.38
  4640.5 1738.14  4689.8 1738.17  4710.8 1739.25  4810.1 1740.29  4866.9 1740.29
  4887.8 1738.68  4909.4 1739.99  4930.4 1736.11  4944.6 1732.34  4994.2 1731.42
  4995.0 1730.47  4995.4 1729.97  5014.1 1730.47  5030.2 1734.24  5122.3 1745.43
  5243.1 1751.06  5271.9 1753.06  5364.8 1753.71  5406.4 1754.93  5634.5 1756.57
#Mann=3,-1,0
  3409.4    0.05       0  4995.0    0.05       0  5014.1    0.05       0
Bank Sta=4995,5014.1
Exp/Cntr=0.3,0.1

Type RM Length L Ch R = 1,116594,398,398,398
BEGIN DESCRIPTION:
Deadman Creek 133.0
END DESCRIPTION:
XS GIS Cut Line= 5
      1620602.62      6870103.94      1621090.12      6870736.50
      1621458.08      6870841.91      1621643.26      6871151.11
      1622005.03      6871338.02
#Sta/Elev= 30
  3458.2 1743.08  4105.0 1740.33  4233.5 1740.44  4279.0 1741.80  4312.7 1741.02
  4317.9 1739.93  4490.7 1739.40  4679.0 1739.36  4716.0 1739.76  4721.8 1740.51
  4817.1 1734.92  4881.3 1738.41  4933.8 1739.31  4955.1 1738.34  4976.5 1731.75
  4984.7 1729.81  4992.1 1729.27  4996.0 1726.96  4996.5 1726.46  5019.9 1726.96
  5028.0 1730.06  5035.7 1731.72  5111.0 1734.73  5116.6 1733.84  5148.3 1736.41
  5170.8 1739.50  5215.8 1741.44  5294.6 1747.56  5349.0 1749.80  5407.2 1750.92
#Mann=3,-1,0
  3458.2    0.05       0  4996.0    0.03       0  5019.9    0.05       0
Bank Sta=4996,5019.9
Exp/Cntr=0.3,0.1

Type RM Length L Ch R = 1,116196,184,184,184
BEGIN DESCRIPTION:
Mapping XS b73a0971
END DESCRIPTION:
XS GIS Cut Line= 5
      1620531.86      6870449.69      1620876.73      6870809.29
      1621300.75      6871295.34      1621415.33      6871486.31
      1621949.82      6871840.04
#Sta/Elev= 30
  3855.8 1741.98  4231.6 1740.48  4281.3 1742.10  4295.4 1740.74  4323.7 1739.87
  4657.1 1737.87  4812.8 1737.91  4876.4 1739.13  4933.3 1730.86  4954.2 1729.96
  4968.4 1730.39  4982.1 1726.05  4982.8 1725.55  5017.0 1726.05  5018.3 1726.26
  5025.5 1731.16  5033.9 1733.67  5055.3 1737.23  5107.1 1739.55  5208.8 1739.54
  5302.8 1737.90  5417.1 1738.05  5453.3 1734.01  5483.4 1736.94  5597.7 1741.84
  5641.1 1745.51  5721.1 1747.06  5778.2 1747.08  5785.0 1747.75  5862.7 1747.49
#Mann=3,-1,0
  3855.8    0.05       0  4982.1    0.03       0  5017.0    0.05       0
Bank Sta=4982.1,5017
Exp/Cntr=0.3,0.1

Type RM Length L Ch R = 1,116012,278,278,278
BEGIN DESCRIPTION:
Mapping XS 7066595c
END DESCRIPTION:
XS GIS Cut Line= 5
      1620401.44      6870823.11      1621102.61      6871301.63
      1621138.39      6871360.02      1621322.52      6871616.01
      1621849.16      6871912.98
#Sta/Elev= 30
  4085.7 1739.90  4623.2 1739.07  4847.5 1737.09  4919.3 1738.17  4933.0 1736.53
  4954.2 1729.46  4977.2 1728.03  4984.0 1726.18  4984.4 1725.68  5004.0 1726.18
  5006.3 1729.16  5027.2 1729.99  5062.8 1736.12  5092.2 1738.34  5113.1 1737.79
  5163.4 1739.01  5234.6 1738.15  5278.8 1739.11  5308.2 1738.18  5344.2 1739.21
  5454.0 1738.13  5475.7 1736.94  5550.9 1737.75  5578.3 1734.12  5599.9 1733.36
  5637.5 1737.34  5711.6 1739.34  5777.6 1743.12  5858.5 1744.24  5923.0 1743.62
#Mann=3,-1,0
  4085.7    0.05       0  4984.0    0.03       0  5004.0    0.05       0
Bank Sta=4984,5004
Exp/Cntr=0.3,0.1