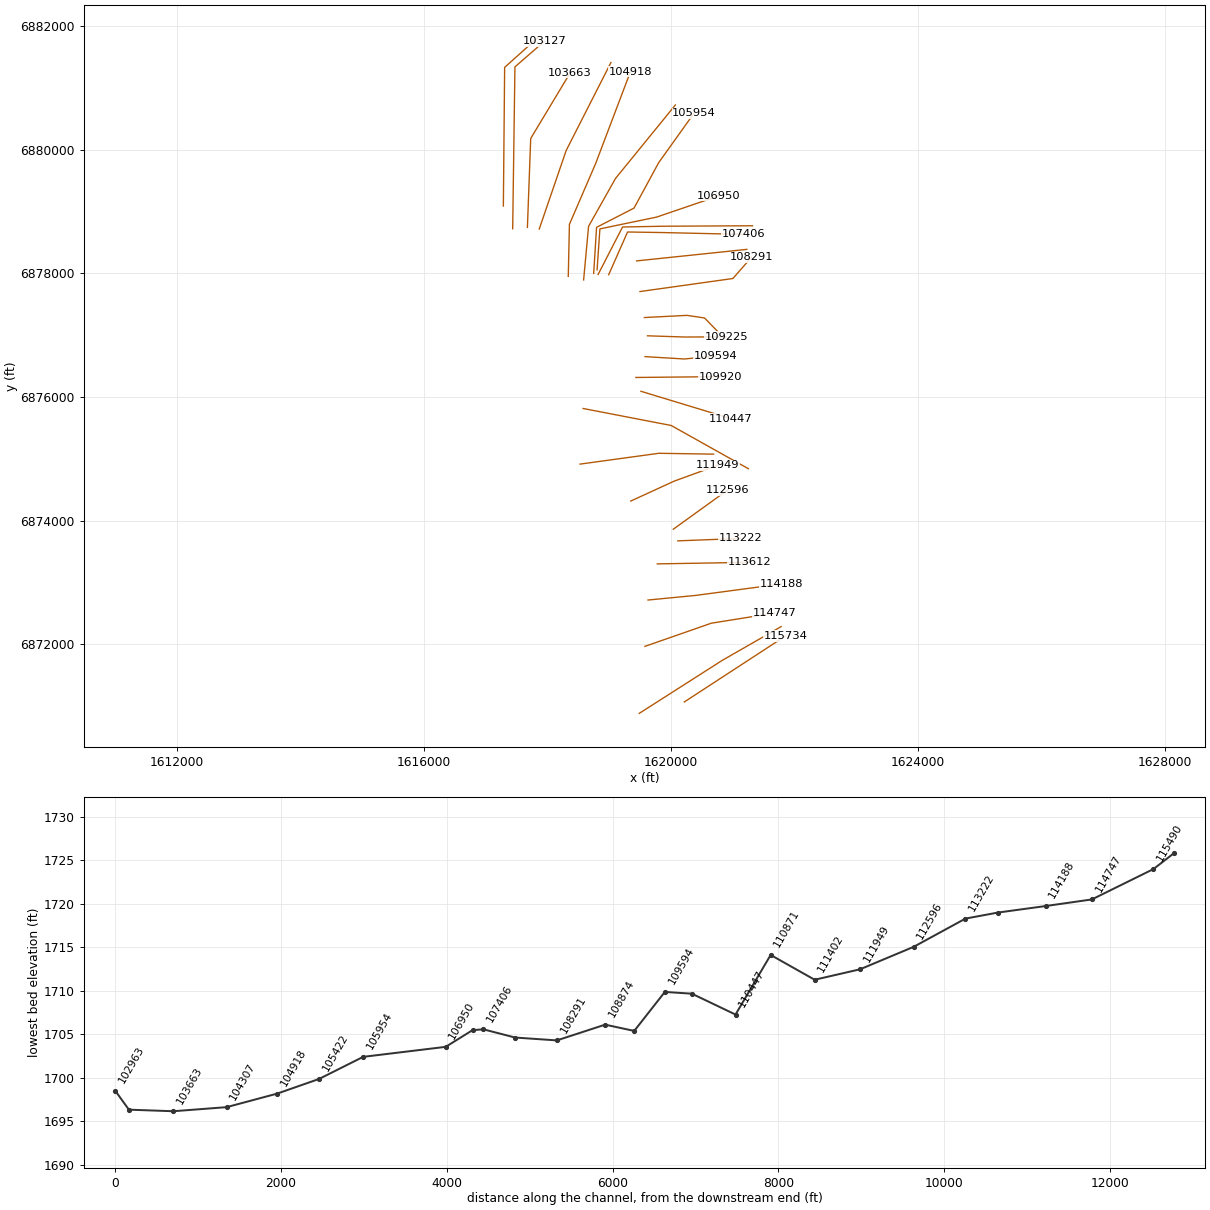
HEC-RAS study Deadman Creek.prj: Deadman Creek Base Level Engineering

--- Deadman Creek.g01 (geometry) --- (continued)

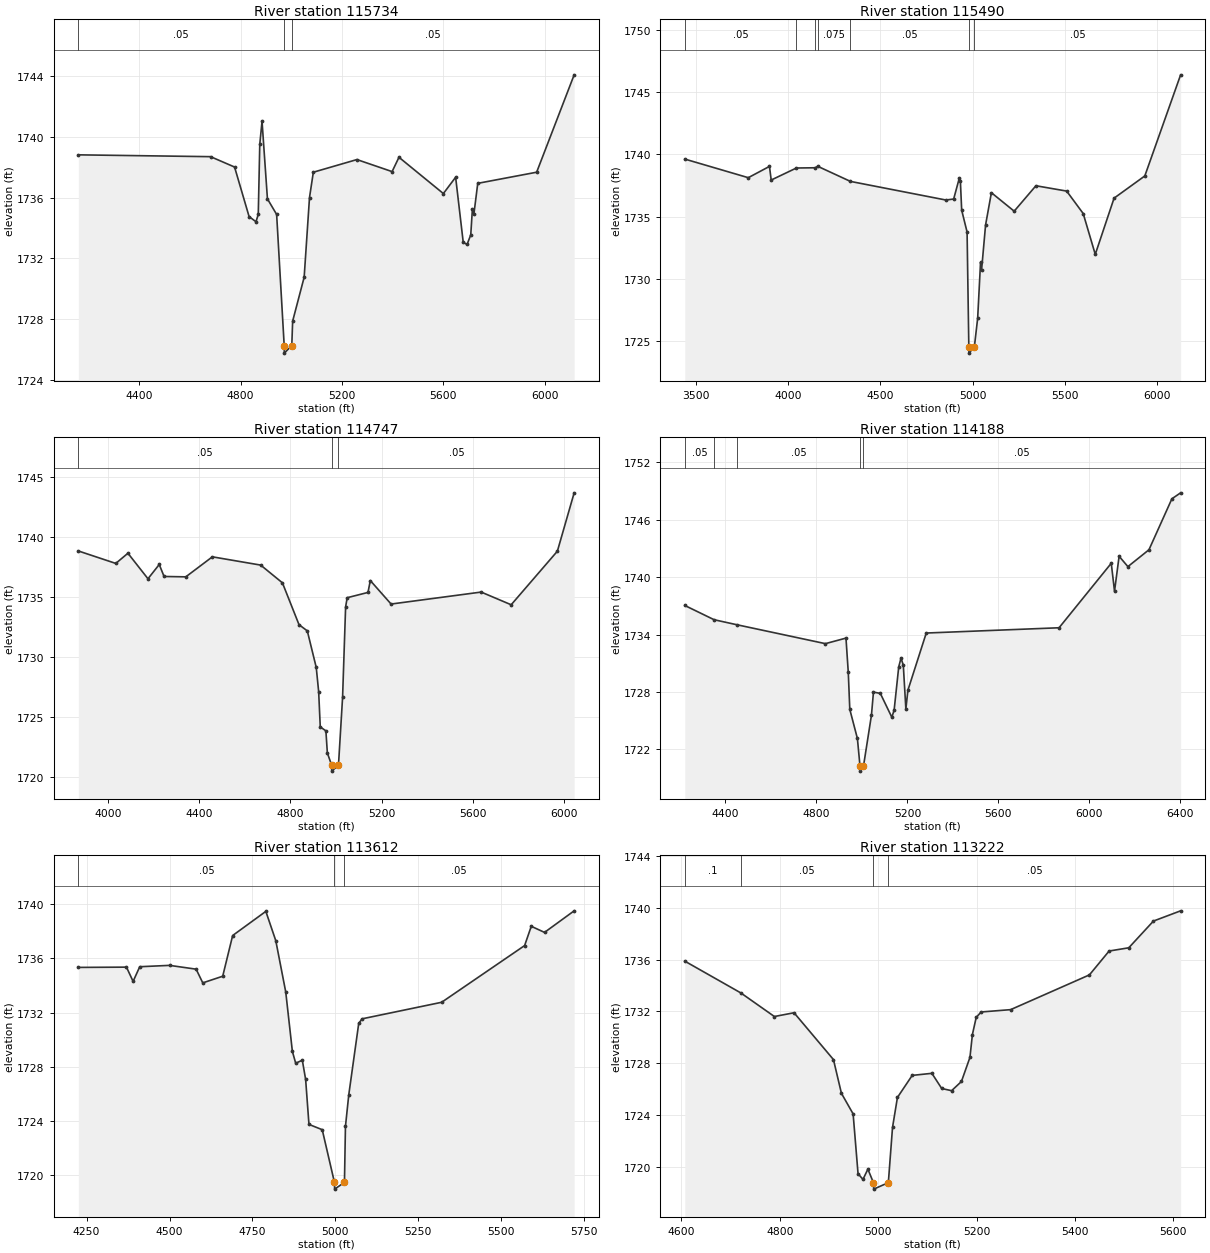
Type RM Length L Ch R = 1,115734,244,244,244
BEGIN DESCRIPTION:
Mapping XS b342220d
END DESCRIPTION:
XS GIS Cut Line= 3
      1620217.74      6871063.62      1621223.72      6871719.30
      1621856.82      6872131.94
#Sta/Elev= 30
  4159.9 1738.80  4681.8 1738.68  4776.4 1738.00  4833.7 1734.75  4860.9 1734.41
  4869.9 1734.89  4875.9 1739.50  4884.8 1741.00  4906.1 1735.91  4942.4 1734.89
  4972.2 1726.29  4972.8 1725.79  5002.2 1726.29  5005.6 1727.89  5051.0 1730.77
  5072.1 1736.00  5087.2 1737.66  5259.2 1738.49  5398.0 1737.70  5425.1 1738.64
  5600.3 1736.26  5648.7 1737.33  5678.7 1733.06  5693.8 1732.92  5708.4 1733.55
  5714.9 1735.25  5720.9 1734.93  5736.0 1736.93  5968.4 1737.66  6116.4 1744.05
#Mann=3,-1,0
  4159.9    0.05       0  4972.2    0.03       0  5002.2    0.05       0
Bank Sta=4972.2,5002.2
Exp/Cntr=0.3,0.1

Type RM Length L Ch R = 1,115490,743,743,743
BEGIN DESCRIPTION:
Deadman Creek 132.0
END DESCRIPTION:
XS GIS Cut Line= 4
      1619488.07      6870878.45      1620833.01      6871737.26
      1621169.83      6871930.37      1621783.86      6872282.42
#Sta/Elev= 30
  3437.9 1739.63  3782.5 1738.13  3897.6 1739.04  3906.9 1737.94  4043.8 1738.91
  4147.2 1738.93  4159.2 1739.05  4337.2 1737.83  4855.3 1736.33  4897.6 1736.41
  4928.1 1738.09  4934.0 1737.86  4941.1 1735.51  4970.4 1733.75  4979.9 1724.49
  4980.5 1723.99  5009.9 1724.49  5027.9 1726.81  5043.5 1731.31  5049.2 1730.71
  5070.8 1734.32  5102.4 1736.92  5226.1 1735.43  5344.1 1737.48  5511.0 1737.05
  5600.8 1735.24  5666.3 1731.95  5768.4 1736.48  5935.3 1738.27  6129.7 1746.42
#Mann=7,-1,0
  3437.9    0.05       0  4043.8   0.075       0  4147.2    0.05       0
  4159.2   0.075       0  4337.2    0.05       0  4979.9    0.03       0
  5009.9    0.05       0
Bank Sta=4979.9,5009.9
Exp/Cntr=0.3,0.1

Type RM Length L Ch R = 1,114747,559,559,559
BEGIN DESCRIPTION:
Deadman Creek 131.0
END DESCRIPTION:
XS GIS Cut Line= 4
      1619579.95      6871962.98      1620655.00      6872338.00
      1621225.47      6872429.27      1621677.71      6872501.63
#Sta/Elev= 30
  3870.2 1738.87  4034.4 1737.83  4087.7 1738.68  4175.6 1736.55  4225.0 1737.74
  4246.2 1736.74  4341.5 1736.71  4458.0 1738.38  4669.9 1737.69  4765.2 1736.21
  4837.9 1732.72  4874.3 1732.20  4913.5 1729.15  4924.1 1727.13  4931.1 1724.19
  4955.8 1723.86  4962.2 1722.02  4980.9 1721.00  4981.5 1720.50  5011.0 1721.00
  5029.0 1726.66  5042.3 1734.21  5049.3 1734.97  5140.4 1735.41  5150.6 1736.40
  5241.7 1734.44  5636.7 1735.44  5768.3 1734.38  5970.9 1738.85  6044.5 1743.72
#Mann=3,-1,0
  3870.2    0.05       0  4980.9    0.05       0  5011.0    0.05       0
Bank Sta=4980.9,5011
Exp/Cntr=0.3,0.1

Type RM Length L Ch R = 1,114188,576,576,576
BEGIN DESCRIPTION:
Deadman Creek 130.0
END DESCRIPTION:
XS GIS Cut Line= 3
      1619629.98      6872713.00      1620405.00      6872788.00
      1621792.96      6872973.19
#Sta/Elev= 30
  4221.8 1737.05  4350.7 1735.56  4449.9 1735.04  4839.7 1733.06  4930.1 1733.64
  4940.2 1730.06  4946.9 1726.19  4980.3 1723.15  4991.8 1720.24  4992.1 1719.74
  5006.9 1720.24  5042.0 1725.58  5050.9 1728.00  5081.1 1727.86  5131.6 1725.37
  5141.7 1726.11  5161.9 1730.63  5171.9 1731.55  5182.0 1730.82  5193.3 1726.23
  5202.2 1728.19  5282.9 1734.17  5866.5 1734.72  6095.9 1741.46  6110.2 1738.54
  6130.4 1742.19  6169.0 1741.11  6261.5 1742.87  6362.4 1748.20  6400.7 1748.82
#Mann=5,-1,0
  4221.8    0.05       0  4350.7    0.12       0  4449.9    0.05       0
  4991.8    0.03       0  5006.9    0.05       0
Bank Sta=4991.8,5006.9
Exp/Cntr=0.3,0.1

Type RM Length L Ch R = 1,113612,390,390,390
BEGIN DESCRIPTION:
Mapping XS 2c884942
END DESCRIPTION:
XS GIS Cut Line= 2
      1619779.90      6873298.09      1621274.29      6873323.12
#Sta/Elev= 30
  4225.1 1735.33  4370.2 1735.35  4390.2 1734.30  4410.2 1735.38  4500.2 1735.48
  4580.2 1735.20  4600.2 1734.19  4660.3 1734.68  4690.3 1737.68  4790.3 1739.46
  4820.3 1737.30  4850.3 1733.52  4870.3 1729.14  4880.3 1728.27  4900.3 1728.49
  4910.3 1727.07  4920.3 1723.76  4960.3 1723.37  4997.1 1719.49  4997.7 1718.99
  5027.3 1719.49  5030.3 1723.61  5040.3 1725.94  5070.3 1731.20  5080.3 1731.54
  5320.3 1732.76  5570.4 1736.94  5590.4 1738.36  5630.4 1737.91  5719.7 1739.50
#Mann=3,-1,0
  4225.1    0.05       0  4997.1    0.05       0  5027.3    0.05       0
Bank Sta=4997.1,5027.3
Exp/Cntr=0.3,0.1

Type RM Length L Ch R = 1,113222,626,626,626
BEGIN DESCRIPTION:
Mapping XS f4df6c46
END DESCRIPTION:
XS GIS Cut Line= 2
      1620113.04      6873670.83      1621120.30      6873709.23
#Sta/Elev= 30
  4606.8 1735.88  4720.7 1733.43  4788.9 1731.61  4828.9 1731.90  4909.0 1728.29
  4925.2 1725.69  4949.0 1724.10  4959.0 1719.49  4969.0 1719.05  4979.0 1719.84
  4990.3 1718.80  4990.9 1718.30  5020.6 1718.80  5029.1 1723.06  5039.1 1725.37
  5069.1 1727.07  5109.1 1727.23  5129.1 1726.06  5149.2 1725.89  5169.2 1726.60
  5186.5 1728.46  5191.5 1730.22  5199.2 1731.54  5209.2 1731.96  5269.2 1732.14
  5429.4 1734.82  5469.4 1736.66  5509.4 1736.91  5559.5 1738.97  5614.8 1739.76
#Mann=4,-1,0
  4606.8     0.1       0  4720.7    0.05       0  4990.3    0.05       0
  5020.6    0.05       0
Bank Sta=4990.3,5020.6
Exp/Cntr=0.3,0.1

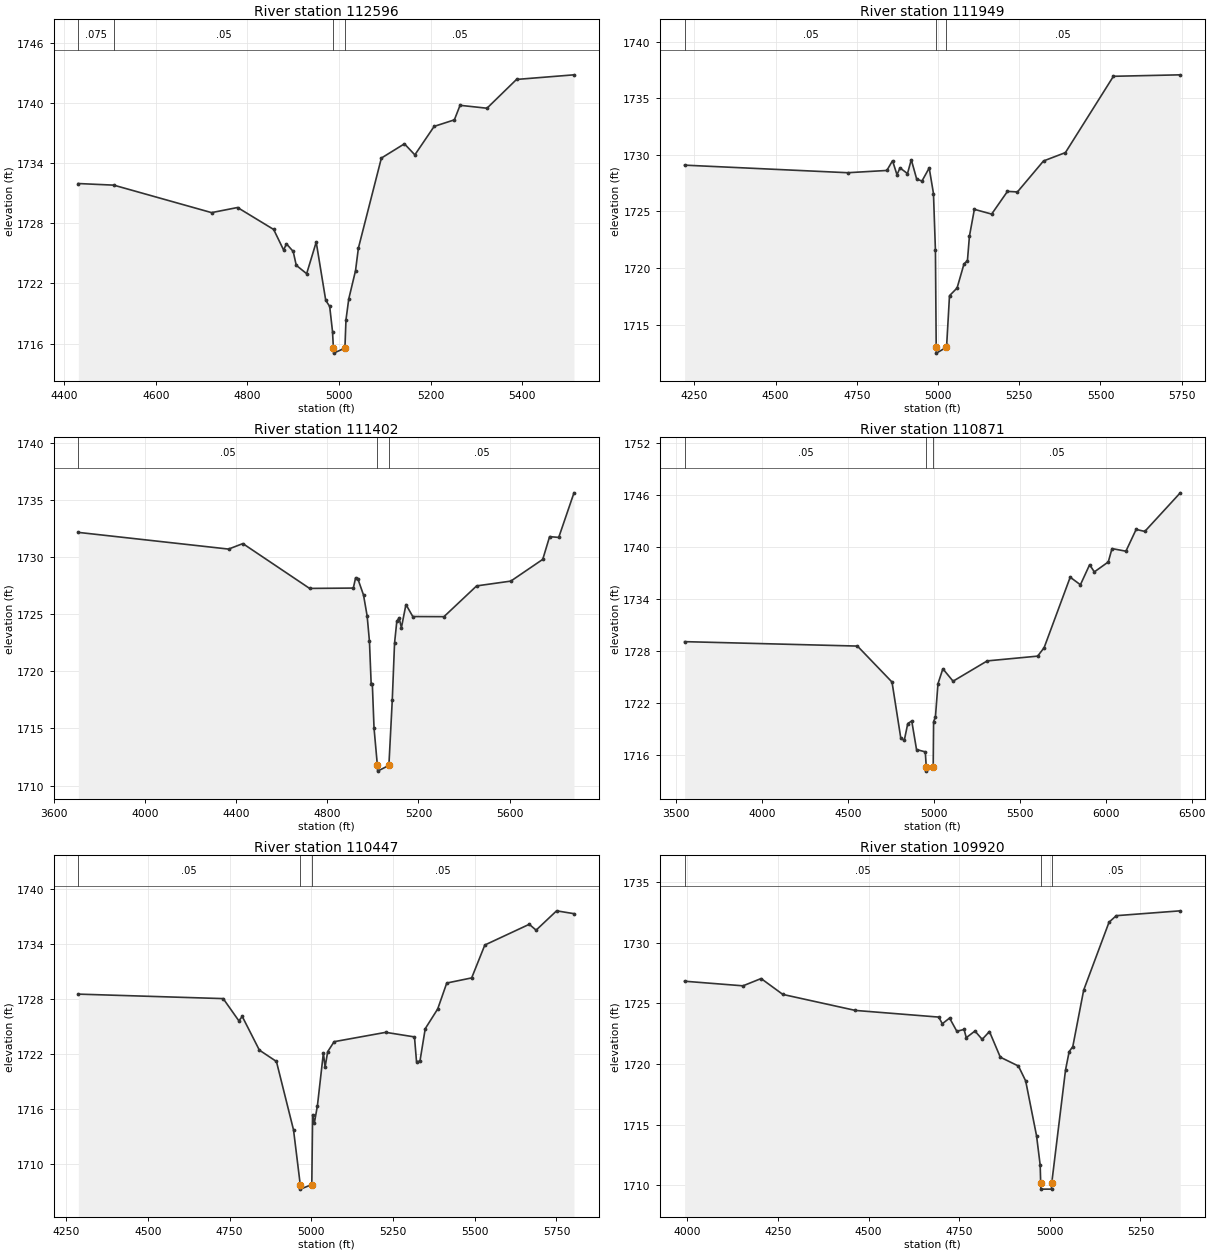
Type RM Length L Ch R = 1,112596,647,647,647
BEGIN DESCRIPTION:
Mapping XS e4c1d31a
END DESCRIPTION:
XS GIS Cut Line= 2
      1620039.06      6873858.81      1620916.80      6874492.19
#Sta/Elev= 30
  4430.6 1731.96  4508.0 1731.80  4721.6 1729.06  4778.3 1729.57  4857.2 1727.38
  4878.9 1725.33  4885.1 1725.95  4899.8 1725.19  4906.5 1723.81  4929.2 1722.97
  4950.1 1726.12  4970.9 1720.31  4979.5 1719.71  4985.7 1717.20  4987.6 1715.55
  4988.1 1715.05  5012.8 1715.55  5015.1 1718.38  5021.2 1720.46  5035.9 1723.26
  5042.2 1725.52  5092.4 1734.50  5142.7 1735.92  5165.5 1734.82  5207.7 1737.66
  5251.8 1738.31  5264.2 1739.76  5323.0 1739.47  5387.5 1742.34  5513.0 1742.80
#Mann=4,-1,0
  4430.6   0.075       0  4508.0    0.05       0  4987.6    0.05       0
  5012.8    0.05       0
Bank Sta=4987.6,5012.8
Exp/Cntr=0.3,0.1

Type RM Length L Ch R = 1,111949,547,547,547
BEGIN DESCRIPTION:
Deadman Creek 129.0
END DESCRIPTION:
XS GIS Cut Line= 3
      1619350.97      6874315.07      1620055.00      6874638.00
      1620760.57      6874894.20
#Sta/Elev= 30
  4220.3 1729.10  4722.2 1728.43  4842.6 1728.63  4860.1 1729.49  4873.8 1728.25
  4883.1 1728.86  4906.1 1728.35  4917.8 1729.58  4934.6 1727.85  4950.8 1727.70
  4972.9 1728.85  4986.1 1726.59  4992.1 1721.56  4994.5 1712.97  4995.1 1712.47
  5024.8 1712.97  5026.8 1713.22  5035.4 1717.55  5058.7 1718.23  5080.0 1720.36
  5090.6 1720.65  5096.7 1722.81  5111.9 1725.19  5165.1 1724.77  5213.8 1726.78
  5244.4 1726.73  5324.7 1729.47  5392.1 1730.21  5539.8 1736.96  5745.5 1737.09
#Mann=3,-1,0
  4220.3    0.05       0  4994.5    0.03       0  5024.8    0.05       0
Bank Sta=4994.5,5024.8
Exp/Cntr=0.3,0.1

Type RM Length L Ch R = 1,111402,531,531,531
BEGIN DESCRIPTION:
Deadman Creek 128.0
END DESCRIPTION:
XS GIS Cut Line= 3
      1618530.00      6874913.00      1619805.00      6875088.00
      1620691.94      6875074.08
#Sta/Elev= 30
  3708.4 1732.15  4367.4 1730.69  4430.1 1731.17  4722.8 1727.25  4914.6 1727.28
  4924.7 1728.19  4934.8 1728.07  4959.3 1726.67  4975.2 1724.84  4985.3 1722.62
  4992.8 1718.91  4997.9 1718.91  5005.4 1715.03  5020.1 1711.77  5021.1 1711.27
  5070.6 1711.77  5085.4 1717.49  5095.4 1722.46  5105.4 1724.39  5115.4 1724.66
  5125.4 1723.81  5145.4 1725.84  5175.4 1724.79  5312.2 1724.78  5455.4 1727.47
  5605.4 1727.89  5745.4 1729.79  5775.5 1731.78  5815.5 1731.71  5882.4 1735.61
#Mann=3,-1,0
  3708.4    0.05       0  5020.1    0.03       0  5070.6    0.05       0
Bank Sta=5020.1,5070.6
Exp/Cntr=0.3,0.1

Type RM Length L Ch R = 1,110871,424,424,424
BEGIN DESCRIPTION:
Deadman Creek 127.0
END DESCRIPTION:
XS GIS Cut Line= 3
      1618580.02      6875813.00      1620005.00      6875538.00
      1621254.98      6874838.01
#Sta/Elev= 30
  3550.0 1729.05  4555.5 1728.54  4756.8 1724.39  4807.8 1717.93  4828.1 1717.67
  4848.5 1719.61  4871.6 1719.90  4899.4 1716.61  4950.3 1716.34  4956.0 1714.62
  4956.8 1714.12  4996.4 1714.62  4998.7 1719.83  5009.3 1720.35  5024.2 1724.20
  5052.6 1725.92  5112.0 1724.49  5310.7 1726.83  5604.0 1727.38  5641.7 1728.35
  5793.5 1736.48  5852.9 1735.61  5906.5 1737.92  5933.9 1737.09  6015.0 1738.24
  6036.7 1739.78  6117.7 1739.48  6177.1 1741.99  6227.6 1741.76  6433.9 1746.21
#Mann=3,-1,0
  3550.0    0.05       0  4956.0    0.05       0  4996.4    0.05       0
Bank Sta=4956,4996.4
Exp/Cntr=0.3,0.1

Type RM Length L Ch R = 1,110447,527,527,527
BEGIN DESCRIPTION:
Mapping XS 8f64d95a
END DESCRIPTION:
XS GIS Cut Line= 2
      1619515.15      6876091.60      1620965.90      6875650.95
#Sta/Elev= 30
  4287.3 1728.55  4730.5 1728.06  4778.3 1725.64  4788.8 1726.11  4841.1 1722.44
  4893.3 1721.20  4945.6 1713.73  4966.1 1707.77  4966.8 1707.27  5001.5 1707.77
  5004.0 1715.40  5009.3 1714.49  5018.7 1716.37  5036.9 1722.12  5042.2 1720.59
  5050.1 1722.27  5069.8 1723.36  5227.7 1724.38  5315.6 1723.88  5321.8 1721.19
  5332.3 1721.23  5348.5 1724.78  5386.6 1726.93  5414.3 1729.76  5490.5 1730.32
  5530.8 1733.91  5666.7 1736.17  5687.6 1735.53  5750.3 1737.64  5803.5 1737.33
#Mann=3,-1,0
  4287.3    0.05       0  4966.1    0.05       0  5001.5    0.05       0
Bank Sta=4966.1,5001.5
Exp/Cntr=0.3,0.1

Type RM Length L Ch R = 1,109920,326,326,326
BEGIN DESCRIPTION:
Mapping XS 997b0aa1
END DESCRIPTION:
XS GIS Cut Line= 2
      1619433.87      6876315.29      1620801.61      6876328.84
#Sta/Elev= 30
  3992.1 1726.83  4153.2 1726.45  4203.2 1727.05  4263.2 1725.74  4463.3 1724.42
  4693.3 1723.87  4703.3 1723.32  4723.3 1723.79  4743.3 1722.70  4763.3 1722.85
  4769.4 1722.17  4793.3 1722.72  4813.3 1722.03  4833.3 1722.68  4863.3 1720.56
  4913.3 1719.83  4933.3 1718.60  4963.3 1714.07  4973.3 1711.66  4974.7 1710.17
  4975.3 1709.67  5004.6 1709.67  5005.2 1710.17  5043.3 1719.51  5053.3 1721.02
  5063.3 1721.43  5093.3 1726.09  5163.3 1731.70  5183.3 1732.24  5359.9 1732.64
#Mann=3,-1,0
  3992.1    0.05       0  4974.7    0.05       0  5005.2    0.05       0
Bank Sta=4974.7,5005.2
Exp/Cntr=0.3,0.1

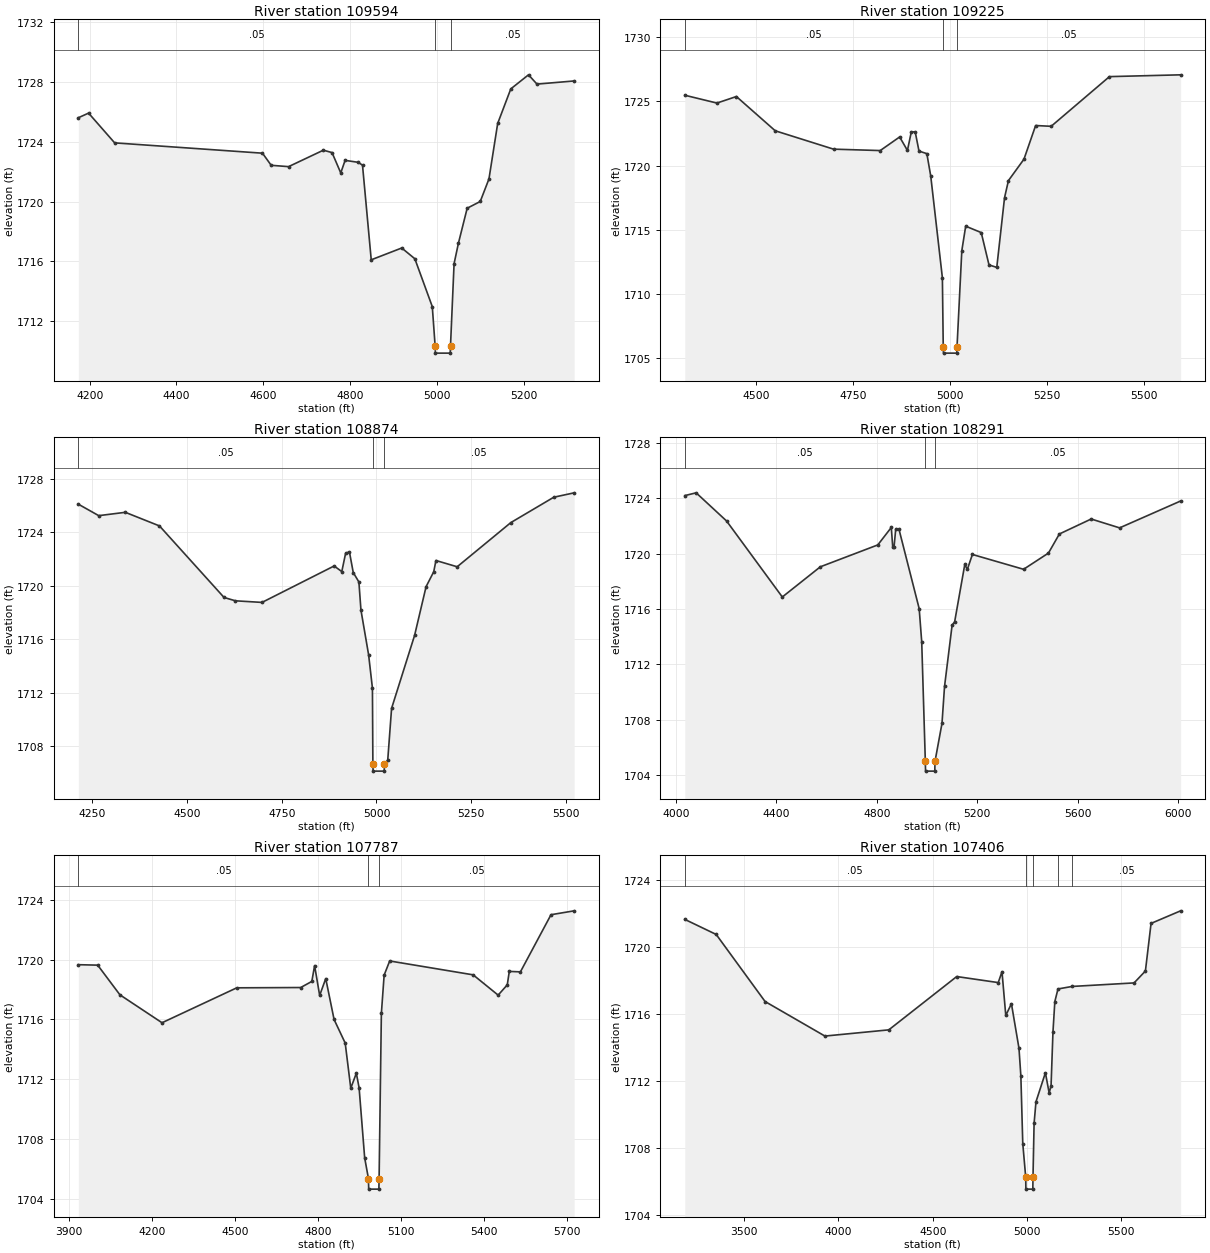
Type RM Length L Ch R = 1,109594,369,369,369
BEGIN DESCRIPTION:
Mapping XS c8ea93c5
END DESCRIPTION:
XS GIS Cut Line= 3
      1619581.44      6876652.65      1620219.08      6876614.14
      1620720.32      6876663.81
#Sta/Elev= 30
  4173.9 1725.61  4197.5 1725.92  4257.6 1723.93  4598.2 1723.24  4618.3 1722.43
  4658.3 1722.34  4738.5 1723.44  4758.5 1723.28  4778.6 1721.92  4788.6 1722.76
  4818.7 1722.63  4828.7 1722.44  4848.8 1716.11  4919.1 1716.90  4949.3 1716.18
  4989.5 1712.98  4996.0 1710.37  4996.7 1709.87  5030.8 1709.87  5031.5 1710.37
  5039.7 1715.85  5049.8 1717.23  5069.9 1719.56  5100.0 1720.01  5120.1 1721.52
  5140.2 1725.23  5170.4 1727.54  5211.2 1728.48  5230.7 1727.86  5316.4 1728.07
#Mann=3,-1,0
  4173.9    0.05       0  4996.0    0.05       0  5031.5    0.05       0
Bank Sta=4996,5031.5
Exp/Cntr=0.3,0.1

Type RM Length L Ch R = 1,109225,351,351,351
BEGIN DESCRIPTION:
Mapping XS be03128e
END DESCRIPTION:
XS GIS Cut Line= 3
      1619622.31      6876989.44      1620229.54      6876969.78
      1620898.18      6876972.87
#Sta/Elev= 30
  4317.4 1725.48  4400.1 1724.87  4450.2 1725.38  4550.2 1722.71  4700.3 1721.28
  4820.4 1721.17  4870.4 1722.23  4890.4 1721.18  4900.4 1722.62  4910.4 1722.63
  4920.2 1721.13  4940.4 1720.93  4950.4 1719.19  4980.4 1711.26  4982.6 1705.89
  4983.3 1705.39  5017.4 1705.39  5018.1 1705.89  5030.4 1713.37  5040.4 1715.28
  5080.4 1714.78  5100.4 1712.26  5120.4 1712.07  5140.4 1717.50  5150.4 1718.83
  5190.4 1720.50  5220.4 1723.12  5260.4 1723.06  5410.4 1726.93  5593.6 1727.07
#Mann=3,-1,0
  4317.4    0.05       0  4982.6    0.05       0  5018.1    0.05       0
Bank Sta=4982.6,5018.1
Exp/Cntr=0.3,0.1

Type RM Length L Ch R = 1,108874,583,583,583
BEGIN DESCRIPTION:
Mapping XS 6030443e
END DESCRIPTION:
XS GIS Cut Line= 4
      1619571.24      6877285.08      1620260.16      6877320.30
      1620545.62      6877277.93      1620775.00      6877041.80
#Sta/Elev= 30
  4213.7 1726.11  4267.5 1725.25  4337.6 1725.50  4427.7 1724.48  4598.0 1719.12
  4628.0 1718.87  4698.1 1718.75  4888.3 1721.48  4908.5 1721.06  4918.5 1722.42
  4928.6 1722.54  4938.7 1720.99  4953.6 1720.28  4959.0 1718.18  4979.2 1714.83
  4989.3 1712.33  4990.5 1706.61  4991.1 1706.11  5020.3 1706.11  5020.9 1706.61
  5029.7 1706.94  5039.8 1710.81  5100.5 1716.28  5130.8 1719.93  5151.0 1721.05
  5156.8 1721.89  5212.8 1721.42  5354.3 1724.73  5467.5 1726.63  5521.3 1726.96
#Mann=3,-1,0
  4213.7    0.05       0  4990.5    0.03       0  5020.9    0.05       0
Bank Sta=4990.5,5020.9
Exp/Cntr=0.3,0.1

Type RM Length L Ch R = 1,108291,504,504,504
BEGIN DESCRIPTION:
Mapping XS 326ada1b
END DESCRIPTION:
XS GIS Cut Line= 4
      1619500.28      6877705.91      1620321.46      6877821.12
      1621003.66      6877916.83      1621304.89      6878260.90
#Sta/Elev= 30
  4035.1 1724.19  4080.3 1724.39  4201.4 1722.36  4423.6 1716.87  4575.1 1719.05
  4804.1 1720.63  4857.8 1721.89  4863.6 1720.45  4868.6 1720.45  4875.4 1721.76
  4888.1 1721.78  4968.9 1716.03  4979.0 1713.63  4993.4 1705.00  4994.3 1704.30
  5031.1 1704.30  5031.9 1705.00  5059.8 1707.75  5069.9 1710.41  5100.1 1714.84
  5110.2 1715.08  5150.6 1719.22  5160.7 1718.86  5180.9 1719.94  5384.8 1718.87
  5483.9 1720.04  5527.5 1721.42  5654.2 1722.50  5767.4 1721.86  6010.5 1723.80
#Mann=3,-1,0
  4035.1    0.05       0  4993.4    0.03       0  5031.9    0.05       0
Bank Sta=4993.4,5031.9
Exp/Cntr=0.3,0.1

Type RM Length L Ch R = 1,107787,381,381,381
BEGIN DESCRIPTION:
Mapping XS ed2f9eb1
END DESCRIPTION:
XS GIS Cut Line= 3
      1619445.39      6878201.90      1620154.87      6878276.11
      1621228.26      6878388.39
#Sta/Elev= 30
  3934.2 1719.67  4004.2 1719.64  4084.6 1717.65  4236.8 1715.78  4506.9 1718.12
  4738.2 1718.14  4778.4 1718.55  4788.4 1719.61  4806.7 1717.61  4828.7 1718.74
  4858.8 1716.00  4899.0 1714.42  4919.2 1711.39  4939.3 1712.40  4949.3 1711.42
  4969.4 1706.73  4983.1 1705.33  4984.0 1704.63  5020.8 1704.63  5021.6 1705.33
  5029.8 1716.40  5039.8 1718.97  5059.9 1719.92  5361.6 1718.99  5452.0 1717.63
  5485.0 1718.32  5492.3 1719.22  5532.5 1719.19  5643.1 1723.02  5726.8 1723.28
#Mann=3,-1,0
  3934.2    0.05       0  4983.1    0.05       0  5021.6    0.05       0
Bank Sta=4983.1,5021.6
Exp/Cntr=0.3,0.1

Type RM Length L Ch R = 1,107406,132,132,132
BEGIN DESCRIPTION:
Mapping XS 6fc512a6
END DESCRIPTION:
XS GIS Cut Line= 4
      1618993.50      6877978.81      1619299.19      6878669.75
      1619858.82      6878660.79      1621171.63      6878630.84
#Sta/Elev= 30
  3185.4 1721.66  3351.9 1720.76  3611.0 1716.76  3928.1 1714.70  4266.8 1715.07
  4626.9 1718.25  4847.0 1717.89  4866.9 1718.54  4886.9 1715.93  4916.9 1716.63
  4956.9 1713.97  4966.9 1712.32  4977.0 1708.29  4992.7 1706.27  4993.5 1705.57
  5030.3 1705.57  5031.2 1706.27  5037.0 1709.49  5047.0 1710.78  5097.0 1712.51
  5117.0 1711.30  5127.0 1711.74  5137.0 1714.93  5147.0 1716.76  5163.7 1717.51
  5239.2 1717.66  5567.1 1717.87  5627.1 1718.58  5657.1 1721.42  5813.8 1722.17
#Mann=5,-1,0
  3185.4    0.05       0  4992.7    0.05       0  5031.2    0.05       0
  5163.7    0.12       0  5239.2    0.05       0
Bank Sta=4992.7,5031.2
Exp/Cntr=0.3,0.1

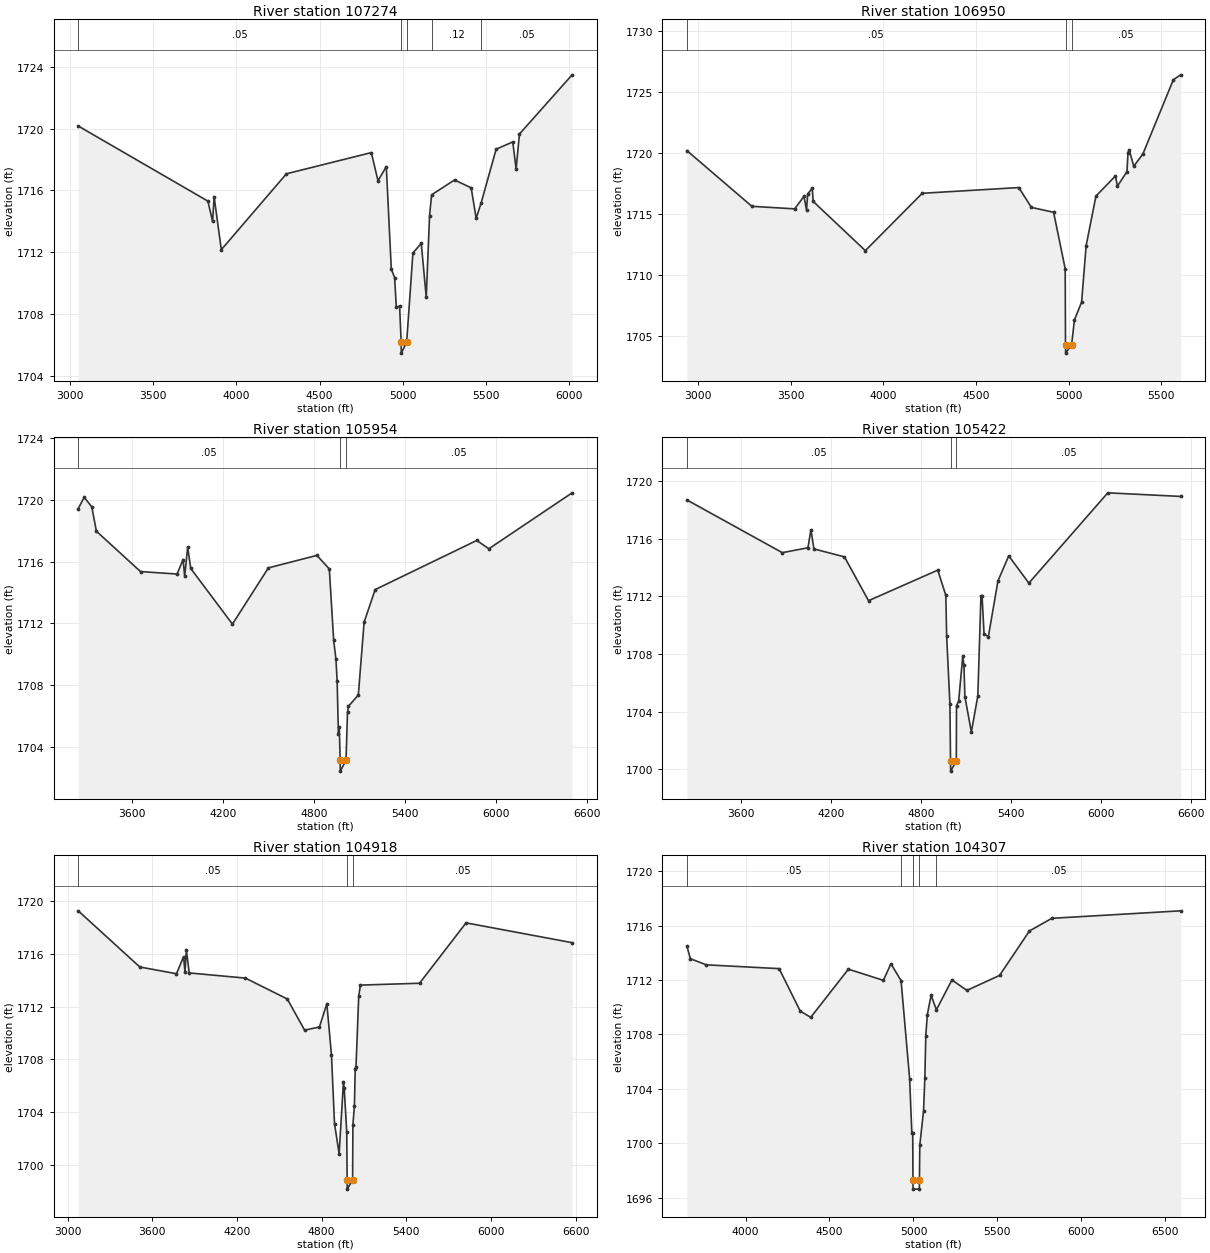
Type RM Length L Ch R = 1,107274,324,324,324
BEGIN DESCRIPTION:
Mapping XS 1e5d38c1
END DESCRIPTION:
XS GIS Cut Line= 5
      1618822.01      6877982.21      1619217.60      6878750.07
      1619298.35      6878752.31      1619880.00      6878763.00
      1621321.58      6878770.73
#Sta/Elev= 30
  3049.2 1720.17  3828.6 1715.31  3856.4 1714.00  3865.7 1715.60  3909.0 1712.17
  4300.5 1717.08  4810.5 1718.45  4850.5 1716.63  4900.5 1717.54  4930.5 1710.92
  4950.5 1710.36  4960.5 1708.46  4980.5 1708.52  4989.8 1706.18  4990.5 1705.48
  5022.8 1706.18  5060.5 1711.96  5110.5 1712.58  5140.5 1709.09  5160.5 1714.38
  5172.7 1715.72  5310.5 1716.68  5410.5 1716.17  5440.5 1714.20  5470.8 1715.21
  5560.5 1718.67  5660.5 1719.14  5680.5 1717.38  5700.5 1719.65  6017.1 1723.48
#Mann=5,-1,0
  3049.2    0.05       0  4989.8    0.05       0  5022.8    0.05       0
  5172.7    0.12       0  5470.8    0.05       0
Bank Sta=4989.8,5022.8
Exp/Cntr=0.3,0.1

Type RM Length L Ch R = 1,106950,996,996,996
BEGIN DESCRIPTION:
Mapping XS c4bea2b9
END DESCRIPTION:
XS GIS Cut Line= 5
      1618805.47      6878056.67      1618851.30      6878719.34
      1619124.44      6878777.13      1619768.86      6878910.68
      1620778.44      6879255.54
#Sta/Elev= 30
  2937.6 1720.20  3288.9 1715.62  3520.3 1715.41  3570.4 1716.44  3584.3 1715.32
  3590.5 1716.63  3615.1 1717.10  3620.3 1716.02  3902.0 1711.98  4209.6 1716.69
  4731.3 1717.16  4799.3 1715.53  4919.2 1715.13  4981.8 1710.49  4983.5 1704.26
  4984.2 1703.56  5016.6 1704.26  5031.7 1706.28  5070.5 1707.75  5095.1 1712.40
  5148.0 1716.46  5253.1 1718.11  5264.2 1717.28  5315.7 1718.47  5321.0 1720.03
  5327.6 1720.27  5352.3 1718.91  5401.6 1719.92  5566.3 1726.02  5606.0 1726.42
#Mann=3,-1,0
  2937.6    0.05       0  4983.5    0.05       0  5016.6    0.05       0
Bank Sta=4983.5,5016.6
Exp/Cntr=0.3,0.1

Type RM Length L Ch R = 1,105954,532,532,532
BEGIN DESCRIPTION:
Deadman Creek 126.0
END DESCRIPTION:
XS GIS Cut Line= 5
      1618750.34      6877998.79      1618797.38      6878745.45
      1619403.49      6879056.23      1619802.70      6879791.86
      1620375.25      6880593.43
#Sta/Elev= 30
  3248.8 1719.45  3288.1 1720.18  3338.2 1719.56  3368.2 1717.98  3658.8 1715.36
  3899.3 1715.20  3939.4 1716.14  3949.4 1715.05  3969.4 1716.95  3989.5 1715.56
  4264.0 1711.95  4500.6 1715.60  4819.9 1716.41  4901.7 1715.53  4930.4 1710.89
  4945.4 1709.67  4953.1 1708.27  4961.6 1704.82  4967.2 1705.27  4973.1 1703.11
  4973.9 1702.41  5011.7 1703.11  5021.4 1706.23  5027.1 1706.61  5092.7 1707.35
  5130.8 1712.08  5203.5 1714.19  5872.3 1717.38  5952.1 1716.84  6500.1 1720.47
#Mann=3,-1,0
  3248.8    0.05       0  4973.1    0.05       0  5011.7    0.05       0
Bank Sta=4973.1,5011.7
Exp/Cntr=0.3,0.1

Type RM Length L Ch R = 1,105422,504,504,504
BEGIN DESCRIPTION:
Deadman Creek 125.0
END DESCRIPTION:
XS GIS Cut Line= 4
      1618587.69      6877893.98      1618667.87      6878761.01
      1619105.00      6879538.00      1620072.16      6880724.90
#Sta/Elev= 30
  3236.9 1718.68  3873.6 1715.02  4044.4 1715.36  4064.4 1716.61  4084.5 1715.28
  4287.8 1714.73  4448.4 1711.69  4910.2 1713.81  4963.8 1712.06  4969.5 1709.21
  4991.2 1704.50  4995.2 1700.57  4996.0 1699.87  5033.8 1700.57  5035.1 1704.42
  5049.4 1704.72  5076.7 1707.83  5084.6 1707.20  5091.1 1705.04  5134.1 1702.58
  5177.2 1705.08  5198.1 1712.04  5205.5 1712.01  5218.9 1709.37  5247.6 1709.20
  5311.5 1713.06  5383.3 1714.80  5517.6 1712.91  6044.0 1719.17  6530.2 1718.92
#Mann=3,-1,0
  3236.9    0.05       0  4995.2    0.05       0  5033.8    0.05       0
Bank Sta=4995.2,5033.8
Exp/Cntr=0.3,0.1

Type RM Length L Ch R = 1,104918,611,611,611
BEGIN DESCRIPTION:
Deadman Creek 124.0
END DESCRIPTION:
XS GIS Cut Line= 4
      1618339.60      6877951.93      1618357.79      6878793.52
      1618781.87      6879776.24      1619344.37      6881260.63
#Sta/Elev= 30
  3075.2 1719.25  3511.4 1715.00  3771.4 1714.49  3821.4 1715.78  3831.4 1714.64
  3841.4 1716.29  3861.5 1714.55  4259.5 1714.16  4556.3 1712.58  4679.3 1710.22
  4784.2 1710.46  4836.7 1712.22  4869.4 1708.36  4891.2 1703.14  4923.9 1700.86
  4954.2 1706.27  4959.7 1705.83  4977.7 1702.55  4980.6 1698.89  4981.5 1698.19
  5019.3 1698.89  5021.3 1703.06  5032.0 1704.46  5037.9 1707.31  5043.2 1707.40
  5062.7 1712.80  5074.7 1713.63  5493.6 1713.77  5823.3 1718.34  6574.7 1716.84
#Mann=3,-1,0
  3075.2    0.05       0  4980.6    0.05       0  5019.3    0.05       0
Bank Sta=4980.6,5019.3
Exp/Cntr=0.3,0.1

Type RM Length L Ch R = 1,104307,644,644,644
BEGIN DESCRIPTION:
Deadman Creek 123.0
END DESCRIPTION:
XS GIS Cut Line= 3
      1617869.59      6878718.14      1618305.00      6879988.00
      1619030.02      6881413.03
#Sta/Elev= 30
  3650.4 1714.51  3671.4 1713.57  3766.5 1713.12  4200.0 1712.84  4325.7 1709.72
  4388.3 1709.26  4612.5 1712.80  4820.8 1711.98  4866.0 1713.20  4926.3 1711.95
  4977.2 1704.76  4990.2 1700.79  4995.6 1700.79  4997.1 1697.33  4997.9 1696.63
  5034.9 1696.63  5035.7 1697.33  5037.7 1699.86  5060.2 1702.39  5067.9 1704.80
  5073.5 1707.92  5082.6 1709.46  5105.0 1710.88  5136.7 1709.82  5229.2 1712.01
  5318.2 1711.24  5512.8 1712.34  5690.8 1715.61  5824.3 1716.54  6591.7 1717.09
#Mann=5,-1,0
  3650.4    0.05       0  4926.3    0.12       0  4997.1    0.07       0
  5035.7    0.12       0  5136.7    0.05       0
Bank Sta=4997.1,5035.7
Exp/Cntr=0.3,0.1

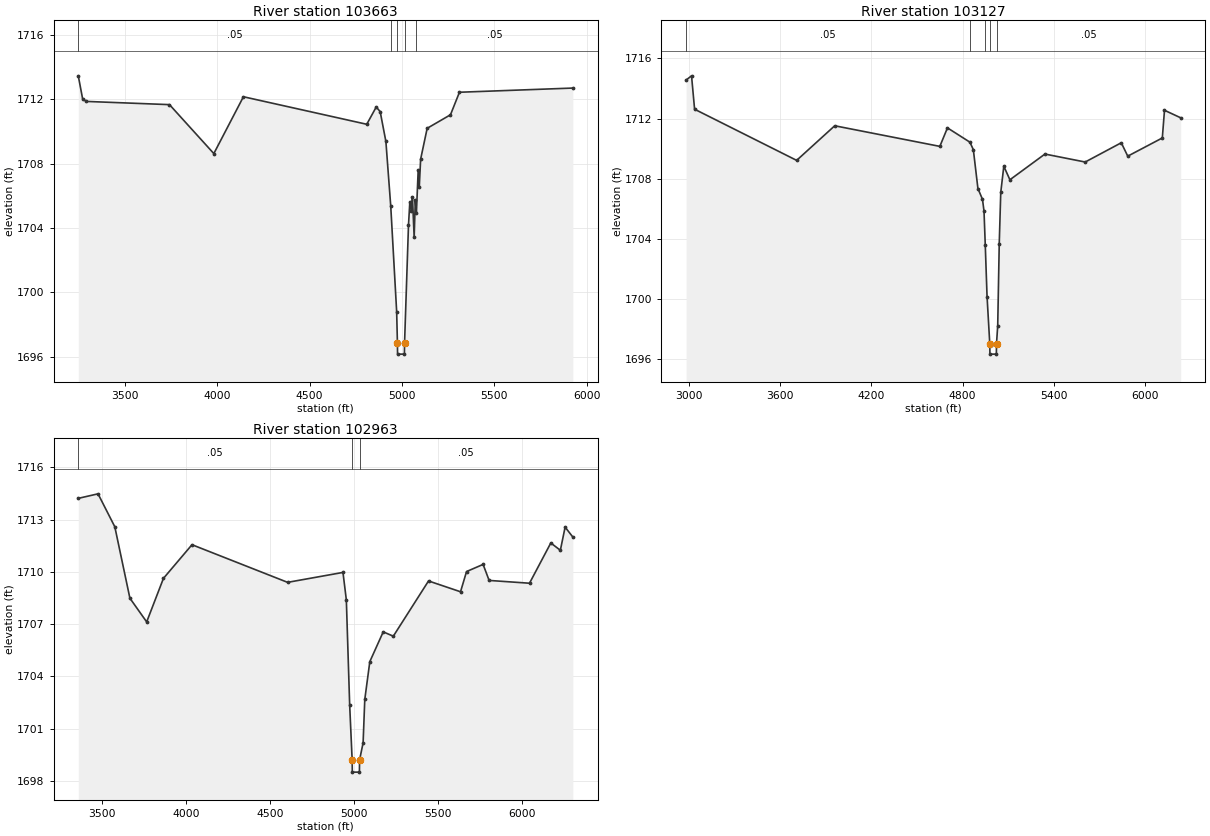
Type RM Length L Ch R = 1,103663,536,536,536
BEGIN DESCRIPTION:
Mapping XS d8653cb6
END DESCRIPTION:
XS GIS Cut Line= 3
      1617677.91      6878744.46      1617731.40      6880183.45
      1618369.27      6881244.26
#Sta/Elev= 30
  3247.9 1713.45  3271.5 1712.02  3291.5 1711.86  3741.8 1711.66  3981.9 1708.62
  4142.1 1712.15  4809.9 1710.44  4861.1 1711.51  4882.5 1711.23  4913.5 1709.37
  4939.8 1705.35  4971.8 1698.80  4975.9 1696.86  4976.7 1696.16  5013.7 1696.16
  5014.6 1696.86  5035.9 1704.18  5043.2 1705.63  5051.5 1705.06  5057.3 1705.93
  5066.6 1703.41  5072.8 1705.75  5078.6 1704.90  5088.4 1707.60  5094.2 1706.53
  5101.6 1708.27  5137.0 1710.19  5263.2 1711.03  5311.8 1712.43  5925.7 1712.69
#Mann=5,-1,0
  3247.9    0.05       0  4939.8    0.12       0  4975.9    0.07       0
  5014.6    0.12       0  5078.6    0.05       0
Bank Sta=4975.9,5014.6
Exp/Cntr=0.3,0.1

Type RM Length L Ch R = 1,103127,164,164,164
BEGIN DESCRIPTION:
Deadman Creek 122.0
END DESCRIPTION:
XS GIS Cut Line= 3
      1617439.66      6878722.41      1617476.12      6881342.25
      1617949.60      6881753.29
#Sta/Elev= 30
  2984.2 1714.56  3019.8 1714.84  3039.8 1712.62  3709.9 1709.22  3959.9 1711.52
  4650.0 1710.15  4700.0 1711.38  4847.4 1710.43  4870.0 1709.93  4900.0 1707.35
  4930.0 1706.63  4940.0 1705.85  4948.2 1703.61  4960.0 1700.17  4977.8 1697.04
  4978.8 1696.34  5021.1 1696.34  5022.1 1697.04  5030.0 1698.23  5040.0 1703.67
  5050.0 1707.09  5070.0 1708.83  5110.0 1707.93  5340.0 1709.64  5604.3 1709.11
  5841.2 1710.39  5883.8 1709.50  6110.7 1710.71  6125.0 1712.55  6231.3 1712.05
#Mann=5,-1,0
  2984.2    0.05       0  4847.4    0.12       0  4948.2    0.05       0
  4977.8    0.05       0  5022.1    0.05       0
Bank Sta=4977.8,5022.1
Exp/Cntr=0.3,0.1

Type RM Length L Ch R = 1,102963,1027,1027,1027
BEGIN DESCRIPTION:
Mapping XS 572de538
END DESCRIPTION:
XS GIS Cut Line= 3
      1617288.67      6879090.17      1617309.53      6881333.90
      1617833.84      6881804.12
#Sta/Elev= 30
  3357.7 1714.22  3475.5 1714.48  3575.5 1712.59  3665.5 1708.49  3765.5 1707.13
  3865.5 1709.63  4035.6 1711.56  4605.6 1709.40  4935.6 1709.97  4955.6 1708.40
  4975.6 1702.34  4990.3 1699.21  4991.3 1698.51  5033.6 1698.51  5034.6 1699.21
  5055.6 1700.19  5065.6 1702.68  5095.6 1704.85  5175.6 1706.56  5235.6 1706.31
  5445.6 1709.48  5636.3 1708.86  5672.2 1710.02  5770.9 1710.43  5806.8 1709.51
  6047.5 1709.35  6174.5 1711.66  6231.4 1711.24  6259.8 1712.57  6305.8 1712.00
#Mann=3,-1,0
  3357.7    0.05       0  4990.3    0.05       0  5034.6    0.05       0
Bank Sta=4990.3,5034.6
Exp/Cntr=0.3,0.1