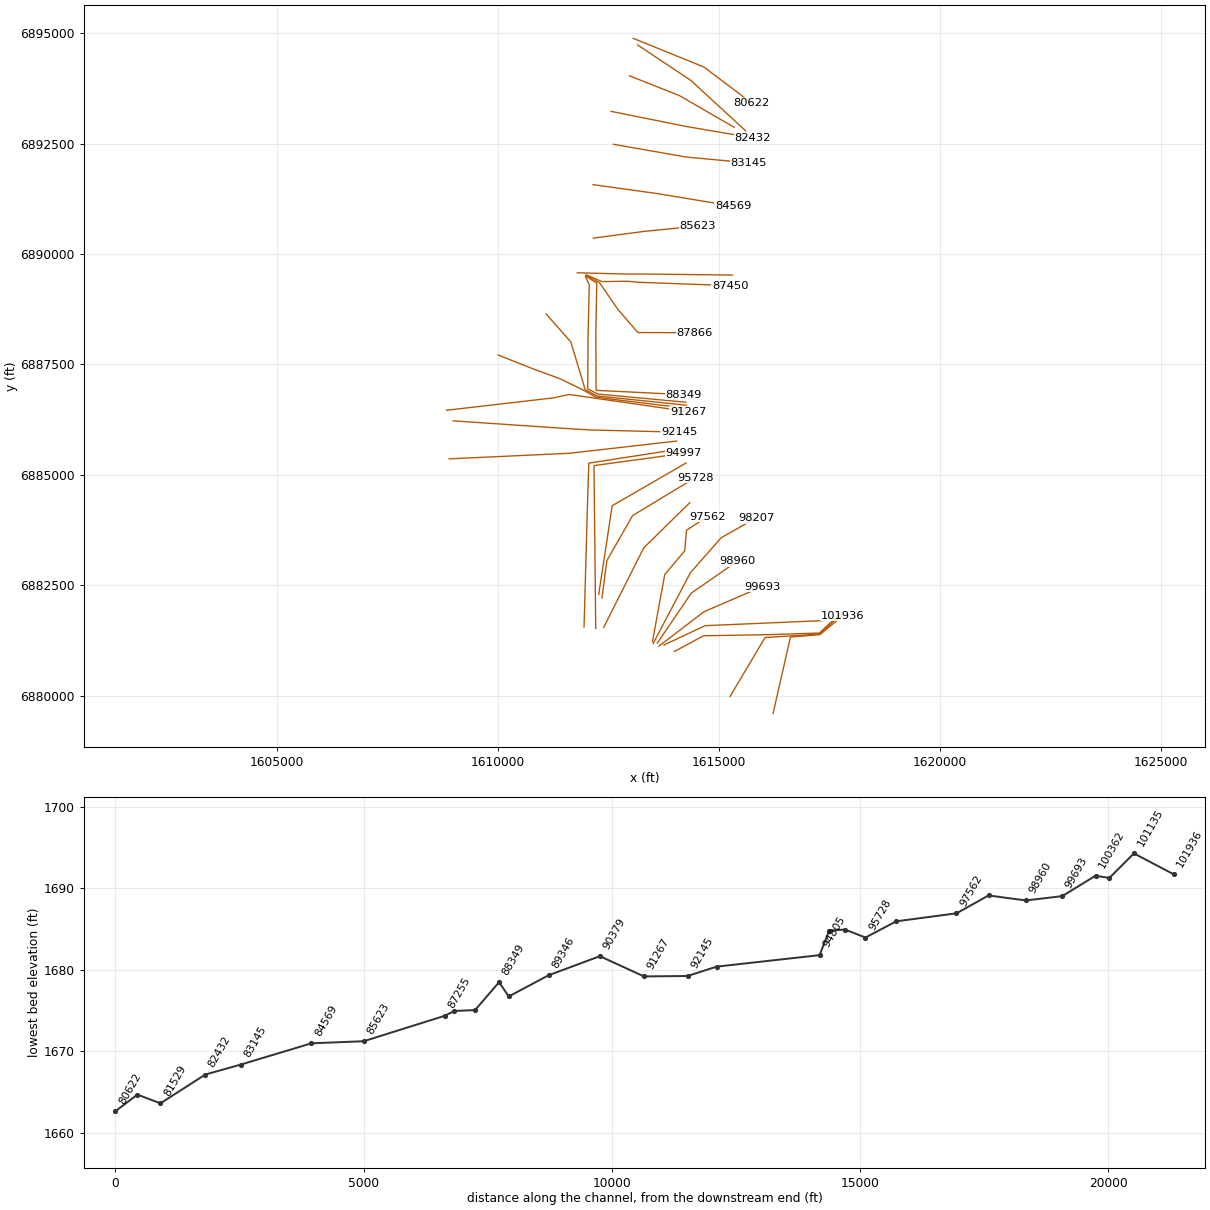
HEC-RAS study Deadman Creek.prj: Deadman Creek Base Level Engineering

--- Deadman Creek.g01 (geometry) --- (continued)

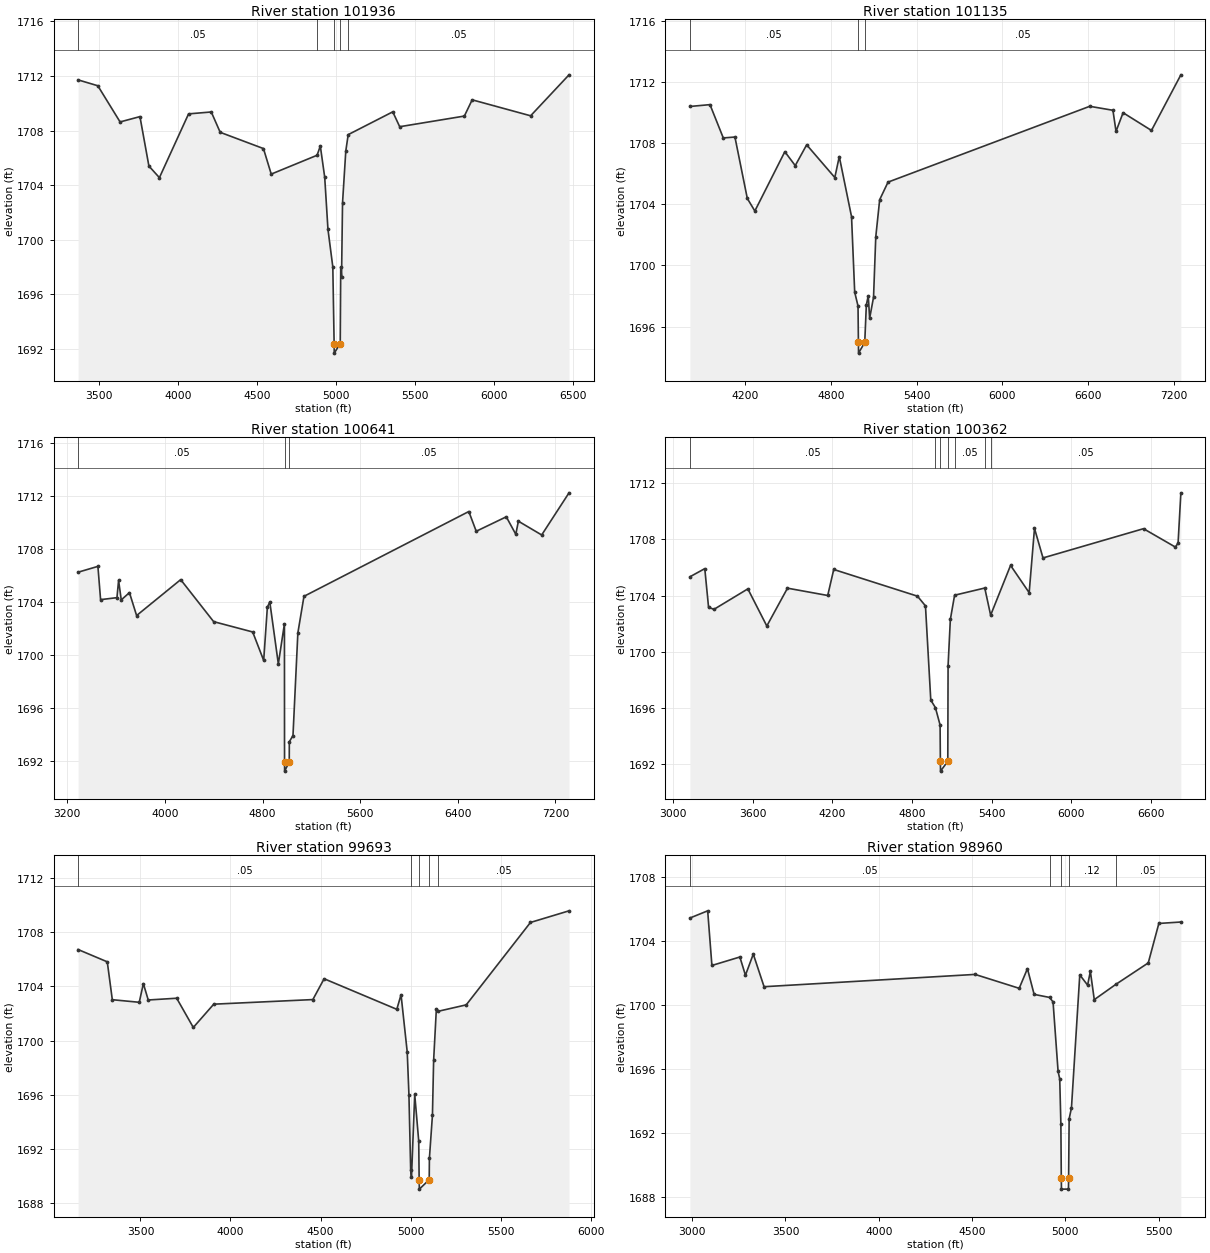
Type RM Length L Ch R = 1,101936,801,801,801
BEGIN DESCRIPTION:
Mapping XS ca27e229
END DESCRIPTION:
XS GIS Cut Line= 4
      1616220.54      6879596.33      1616613.74      6881325.05
      1617280.33      6881379.78      1617791.99      6881804.07
#Sta/Elev= 30
  3367.9 1711.71  3492.7 1711.28  3633.6 1708.63  3759.3 1709.02  3816.0 1705.40
  3882.4 1704.55  4067.0 1709.22  4210.6 1709.36  4267.1 1707.87  4540.8 1706.68
  4590.0 1704.81  4880.2 1706.19  4900.6 1706.87  4928.4 1704.58  4948.9 1700.77
  4979.7 1698.01  4988.0 1692.40  4988.8 1691.70  5026.7 1692.40  5029.8 1698.01
  5034.9 1697.27  5041.2 1702.71  5061.8 1706.50  5077.0 1707.70  5359.0 1709.37
  5402.9 1708.28  5812.1 1709.06  5861.4 1710.25  6231.3 1709.08  6474.3 1712.08
#Mann=5,-1,0
  3367.9    0.05       0  4880.2    0.12       0  4988.0    0.07       0
  5026.7    0.12       0  5077.0    0.05       0
Bank Sta=4988,5026.7
Exp/Cntr=0.3,0.1

Type RM Length L Ch R = 1,101135,494,494,494
BEGIN DESCRIPTION:
Mapping XS 3b6e5706
END DESCRIPTION:
XS GIS Cut Line= 4
      1615245.41      6879977.50      1616039.49      6881314.53
      1617268.09      6881392.25      1617747.44      6881826.03
#Sta/Elev= 30
  3815.4 1710.40  3955.6 1710.52  4048.6 1708.34  4130.0 1708.40  4216.6 1704.38
  4269.3 1703.56  4478.9 1707.44  4551.7 1706.53  4631.6 1707.89  4828.4 1705.75
  4859.6 1707.12  4945.3 1703.19  4967.4 1698.25  4990.7 1697.34  4993.4 1694.96
  4994.3 1694.26  5037.7 1694.96  5048.8 1697.41  5062.2 1698.01  5072.0 1696.54
  5099.2 1697.92  5114.8 1701.87  5142.1 1704.30  5200.5 1705.45  6610.8 1710.41
  6773.0 1710.15  6794.6 1708.77  6844.0 1709.99  7042.4 1708.83  7248.0 1712.47
#Mann=3,-1,0
  3815.4    0.05       0  4993.4    0.05       0  5037.7    0.05       0
Bank Sta=4993.4,5037.7
Exp/Cntr=0.3,0.1

Type RM Length L Ch R = 1,100641,279,279,279
BEGIN DESCRIPTION:
Mapping XS 08b4d7ca
END DESCRIPTION:
XS GIS Cut Line= 5
      1613984.75      6880997.09      1614646.45      6881354.36
      1616141.24      6881380.41      1617271.45      6881416.86
      1617740.08      6881859.46
#Sta/Elev= 30
  3288.8 1706.26  3451.2 1706.70  3473.1 1704.19  3607.3 1704.34  3620.6 1705.64
  3642.5 1704.17  3709.6 1704.72  3768.2 1702.99  4129.4 1705.70  4399.4 1702.53
  4719.4 1701.75  4809.5 1699.60  4839.5 1703.61  4859.5 1704.02  4929.5 1699.34
  4979.5 1702.37  4980.3 1691.95  4981.1 1691.25  5019.0 1691.95  5019.5 1693.47
  5049.5 1693.93  5089.5 1701.68  5139.5 1704.44  6490.1 1710.84  6550.9 1709.35
  6797.1 1710.44  6875.2 1709.12  6896.2 1710.11  7087.2 1709.07  7311.2 1712.25
#Mann=3,-1,0
  3288.8    0.05       0  4980.3    0.05       0  5019.0    0.05       0
Bank Sta=4980.3,5019
Exp/Cntr=0.3,0.1

Type RM Length L Ch R = 1,100362,669,669,669
BEGIN DESCRIPTION:
Mapping XS b852eb52
END DESCRIPTION:
XS GIS Cut Line= 3
      1613750.43      6881144.70      1614681.70      6881582.65
      1617345.90      6881697.90
#Sta/Elev= 30
  3128.1 1705.34  3239.9 1705.92  3268.2 1703.18  3308.3 1703.02  3564.1 1704.48
  3706.9 1701.84  3862.5 1704.53  4165.4 1704.01  4210.6 1705.86  4841.1 1703.96
  4901.2 1703.27  4941.2 1696.57  4975.9 1696.04  5011.3 1694.80  5013.4 1692.22
  5014.6 1691.52  5069.3 1692.22  5071.4 1699.01  5088.6 1702.31  5120.5 1704.03
  5347.6 1704.54  5391.8 1702.61  5541.8 1706.15  5681.9 1704.21  5722.0 1708.78
  5786.0 1706.68  6542.7 1708.76  6783.0 1707.45  6803.0 1707.75  6823.9 1711.31
#Mann=7,-1,0
  3128.1    0.05       0  4975.9    0.12       0  5013.4    0.07       0
  5069.3    0.12       0  5120.5    0.05       0  5347.6    0.12       0
  5391.8    0.05       0
Bank Sta=5013.4,5069.3
Exp/Cntr=0.3,0.1

Type RM Length L Ch R = 1,99693,733,733,733
BEGIN DESCRIPTION:
Mapping XS 9a358b55
END DESCRIPTION:
XS GIS Cut Line= 3
      1613636.09      6881119.89      1614661.36      6881901.27
      1615981.69      6882470.03
#Sta/Elev= 30
  3153.6 1706.73  3315.7 1705.82  3343.7 1703.02  3493.3 1702.83  3516.1 1704.21
  3543.2 1703.00  3701.2 1703.13  3793.5 1700.97  3907.0 1702.69  4457.5 1703.03
  4520.1 1704.57  4923.8 1702.31  4947.3 1703.39  4981.7 1699.15  4991.1 1696.01
  5000.8 1690.46  5005.3 1689.88  5023.3 1696.02  5045.5 1692.57  5047.9 1689.72
  5049.1 1689.02  5103.8 1689.72  5104.8 1691.29  5121.7 1694.48  5128.3 1698.53
  5143.5 1702.35  5155.2 1702.17  5309.4 1702.64  5666.1 1708.73  5880.3 1709.59
#Mann=5,-1,0
  3153.6    0.05       0  5000.8    0.12       0  5047.9    0.05       0
  5103.8    0.12       0  5155.2    0.05       0
Bank Sta=5047.9,5103.8
Exp/Cntr=0.3,0.1

Type RM Length L Ch R = 1,98960,753,753,753
BEGIN DESCRIPTION:
Mapping XS 1318c319
END DESCRIPTION:
XS GIS Cut Line= 3
      1613601.39      6881189.33      1614369.86      6882321.58
      1615407.05      6883040.15
#Sta/Elev= 30
  2988.4 1705.46  3083.5 1705.91  3106.1 1702.49  3255.9 1703.02  3285.8 1701.88
  3327.8 1703.20  3385.6 1701.16  4516.2 1701.93  4752.4 1701.06  4796.6 1702.29
  4832.4 1700.68  4914.8 1700.49  4933.8 1700.21  4960.8 1695.86  4969.6 1695.39
  4975.7 1692.58  4978.0 1689.19  4978.9 1688.49  5016.3 1688.49  5017.2 1689.19
  5020.0 1692.89  5032.4 1693.57  5077.0 1701.90  5118.9 1701.26  5133.7 1702.12
  5154.7 1700.35  5269.3 1701.30  5443.9 1702.65  5500.6 1705.12  5618.6 1705.21
#Mann=5,-1,0
  2988.4    0.05       0  4914.8    0.12       0  4978.0    0.07       0
  5017.2    0.12       0  5269.3    0.05       0
Bank Sta=4978,5017.2
Exp/Cntr=0.3,0.1

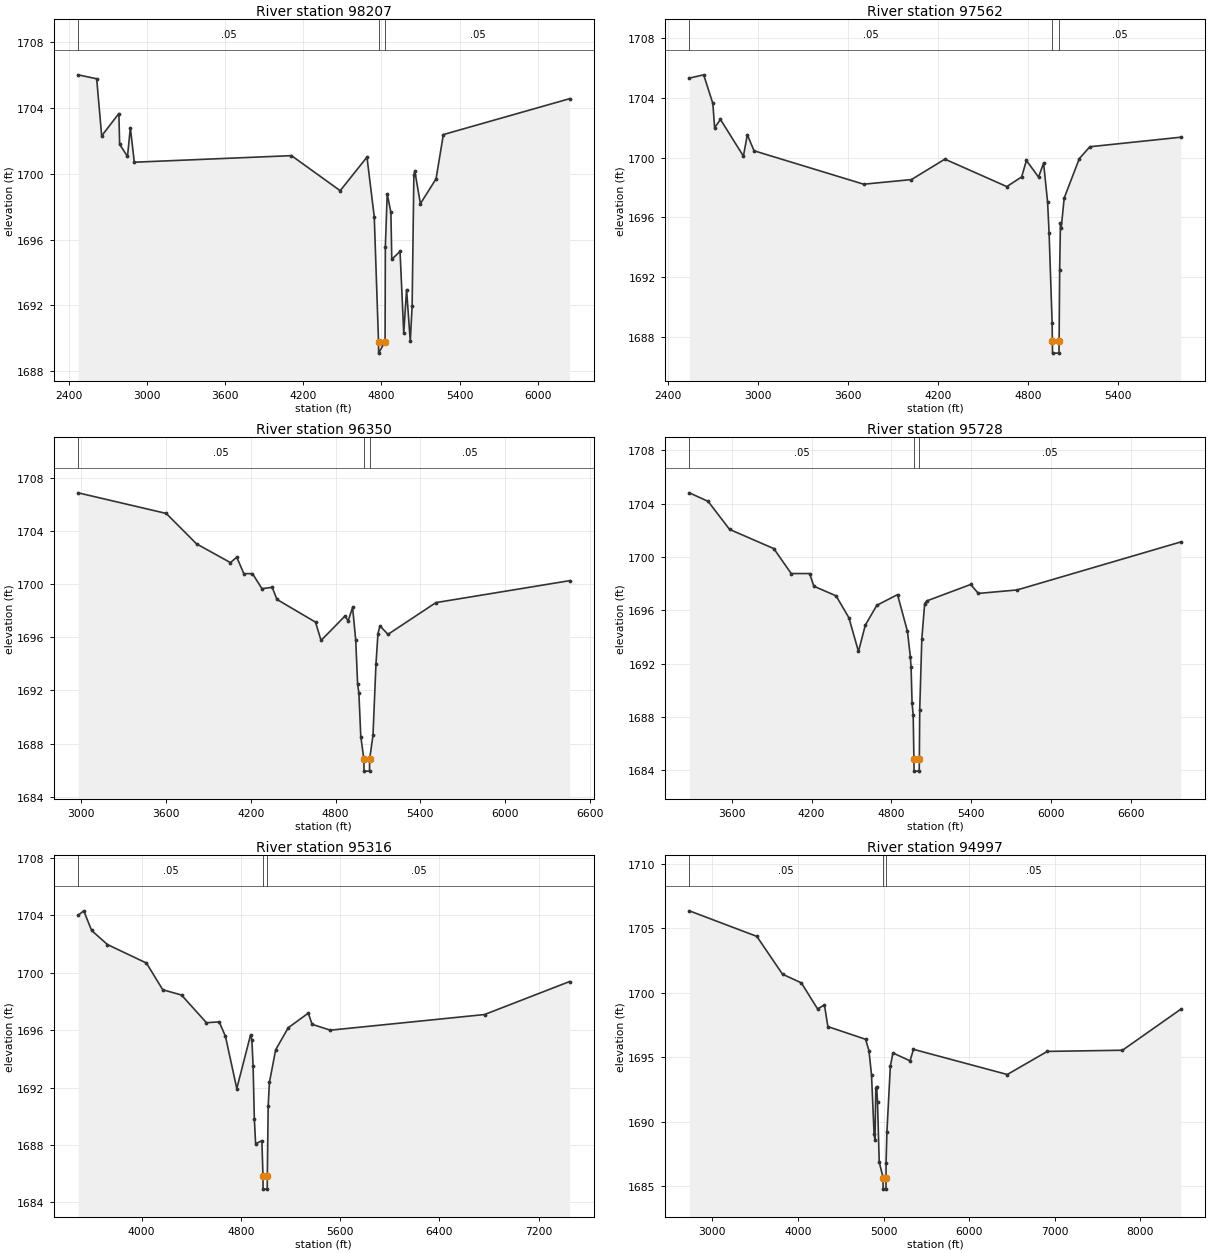
Type RM Length L Ch R = 1,98207,645,645,645
BEGIN DESCRIPTION:
Mapping XS 278394c9
END DESCRIPTION:
XS GIS Cut Line= 4
      1613504.20      6881175.50      1614348.98      6882782.64
      1615043.99      6883573.51      1615835.91      6884022.60
#Sta/Elev= 30
  2467.5 1706.01  2610.2 1705.77  2648.7 1702.30  2780.9 1703.66  2786.7 1701.79
  2847.1 1701.05  2869.1 1702.79  2899.6 1700.70  4108.1 1701.10  4482.5 1698.97
  4688.4 1701.01  4744.4 1697.39  4777.2 1689.80  4778.2 1689.10  4827.6 1689.80
  4829.7 1695.55  4844.0 1698.78  4872.4 1697.65  4879.1 1694.80  4942.7 1695.28
  4971.1 1690.31  4992.9 1692.96  5021.4 1689.81  5035.6 1691.96  5049.1 1699.95
  5056.5 1700.15  5099.2 1698.18  5219.7 1699.69  5275.7 1702.38  6246.4 1704.56
#Mann=3,-1,0
  2467.5    0.05       0  4777.2    0.05       0  4827.6    0.05       0
Bank Sta=4777.2,4827.6
Exp/Cntr=0.3,0.1

Type RM Length L Ch R = 1,97562,1212,1212,1212
BEGIN DESCRIPTION:
Mapping XS 664b2dba
END DESCRIPTION:
XS GIS Cut Line= 5
      1613490.30      6881224.13      1613768.63      6882742.25
      1614220.04      6883277.43      1614261.39      6883745.19
      1614729.16      6884050.26
#Sta/Elev= 30
  2544.6 1705.34  2640.0 1705.56  2701.0 1703.64  2712.8 1702.02  2751.9 1702.57
  2904.4 1700.11  2930.4 1701.54  2975.5 1700.47  3705.0 1698.23  4022.7 1698.54
  4245.6 1699.91  4657.8 1698.07  4756.6 1698.72  4788.1 1699.82  4869.0 1698.71
  4902.7 1699.64  4929.3 1697.02  4939.3 1694.94  4959.4 1688.95  4961.1 1687.71
  4962.2 1686.91  5005.0 1686.91  5006.0 1687.71  5009.6 1692.51  5014.7 1695.61
  5019.7 1695.27  5039.7 1697.30  5140.1 1699.94  5210.4 1700.74  5816.2 1701.38
#Mann=3,-1,0
  2544.6    0.05       0  4961.1    0.03       0  5006.0    0.05       0
Bank Sta=4961.1,5006
Exp/Cntr=0.3,0.1

Type RM Length L Ch R = 1,96350,622,622,622
BEGIN DESCRIPTION:
Deadman Creek 119.0
END DESCRIPTION:
XS GIS Cut Line= 3
      1612384.70      6881540.91      1613294.49      6883347.79
      1614333.82      6884367.32
#Sta/Elev= 30
  2977.0 1706.87  3600.7 1705.32  3815.3 1703.03  4055.1 1701.62  4099.8 1702.03
  4150.0 1700.79  4211.3 1700.79  4278.3 1699.66  4350.9 1699.76  4384.2 1698.85
  4657.6 1697.14  4696.6 1695.76  4865.9 1697.60  4888.3 1697.23  4919.8 1698.25
  4942.1 1695.77  4955.4 1692.46  4964.4 1691.81  4977.8 1688.53  4999.7 1686.83
  5000.6 1685.93  5039.6 1685.93  5040.5 1686.83  5064.2 1688.63  5085.3 1693.99
  5099.4 1696.28  5113.6 1696.86  5170.2 1696.22  5509.6 1698.61  6455.9 1700.26
#Mann=3,-1,0
  2977.0    0.05       0  4999.7    0.05       0  5040.5    0.05       0
Bank Sta=4999.7,5040.5
Exp/Cntr=0.3,0.1

Type RM Length L Ch R = 1,95728,412,412,412
BEGIN DESCRIPTION:
Mapping XS f90ac29c
END DESCRIPTION:
XS GIS Cut Line= 4
      1612348.11      6882207.99      1612456.62      6883054.36
      1613040.94      6884076.92      1614466.25      6884939.44
#Sta/Elev= 30
  3280.3 1704.80  3421.5 1704.16  3582.8 1702.06  3915.5 1700.62  4046.5 1698.75
  4185.2 1698.75  4216.8 1697.80  4383.8 1697.08  4480.3 1695.44  4552.4 1692.91
  4604.1 1694.89  4690.6 1696.37  4846.0 1697.17  4920.9 1694.42  4942.4 1692.53
  4948.2 1691.72  4955.5 1689.06  4964.0 1688.13  4969.5 1684.84  4970.5 1683.94
  5009.5 1683.94  5010.4 1684.84  5013.1 1688.51  5028.8 1693.83  5050.4 1696.50
  5066.3 1696.70  5396.2 1697.93  5454.4 1697.26  5745.4 1697.52  6977.3 1701.12
#Mann=3,-1,0
  3280.3    0.05       0  4969.5    0.05       0  5010.4    0.05       0
Bank Sta=4969.5,5010.4
Exp/Cntr=0.3,0.1

Type RM Length L Ch R = 1,95316,319,319,319
BEGIN DESCRIPTION:
Mapping XS 6a9ade57
END DESCRIPTION:
XS GIS Cut Line= 3
      1612273.82      6882293.64      1612579.37      6884300.54
      1614250.96      6885268.21
#Sta/Elev= 30
  3488.2 1704.01  3533.7 1704.32  3597.2 1702.95  3724.4 1701.97  4038.8 1700.68
  4170.3 1698.82  4321.7 1698.45  4522.6 1696.52  4625.5 1696.58  4676.1 1695.56
  4767.1 1691.93  4878.4 1695.68  4888.5 1695.35  4898.6 1693.50  4908.7 1689.80
  4918.9 1688.08  4969.4 1688.30  4978.2 1685.82  4979.0 1684.92  5012.4 1684.92
  5013.3 1685.82  5020.0 1690.68  5030.1 1692.36  5080.7 1694.64  5181.9 1696.17
  5343.7 1697.19  5374.0 1696.41  5521.0 1696.00  6763.8 1697.09  7449.7 1699.39
#Mann=3,-1,0
  3488.2    0.05       0  4978.2    0.05       0  5013.3    0.05       0
Bank Sta=4978.2,5013.3
Exp/Cntr=0.3,0.1

Type RM Length L Ch R = 1,94997,192,192,192
BEGIN DESCRIPTION:
Deadman Creek 118.0
END DESCRIPTION:
XS GIS Cut Line= 3
      1612206.07      6881519.49      1612167.09      6885209.43
      1614200.87      6885487.08
#Sta/Elev= 30
  2730.9 1706.34  3519.5 1704.36  3819.5 1701.43  4039.5 1700.76  4229.5 1698.74
  4309.5 1699.05  4349.5 1697.37  4789.5 1696.39  4829.5 1695.51  4859.5 1693.62
  4889.5 1689.04  4899.5 1688.60  4909.5 1692.59  4919.5 1692.73  4929.5 1691.50
  4949.5 1686.88  4994.2 1685.68  4995.0 1684.78  5028.4 1684.78  5029.3 1685.68
  5029.5 1686.84  5039.5 1689.24  5079.5 1694.30  5109.5 1695.33  5309.6 1694.72
  5349.6 1695.61  6445.8 1693.66  6913.5 1695.45  7791.6 1695.54  8473.7 1698.72
#Mann=3,-1,0
  2730.9    0.05       0  4994.2    0.05       0  5029.3    0.05       0
Bank Sta=4994.2,5029.3
Exp/Cntr=0.3,0.1

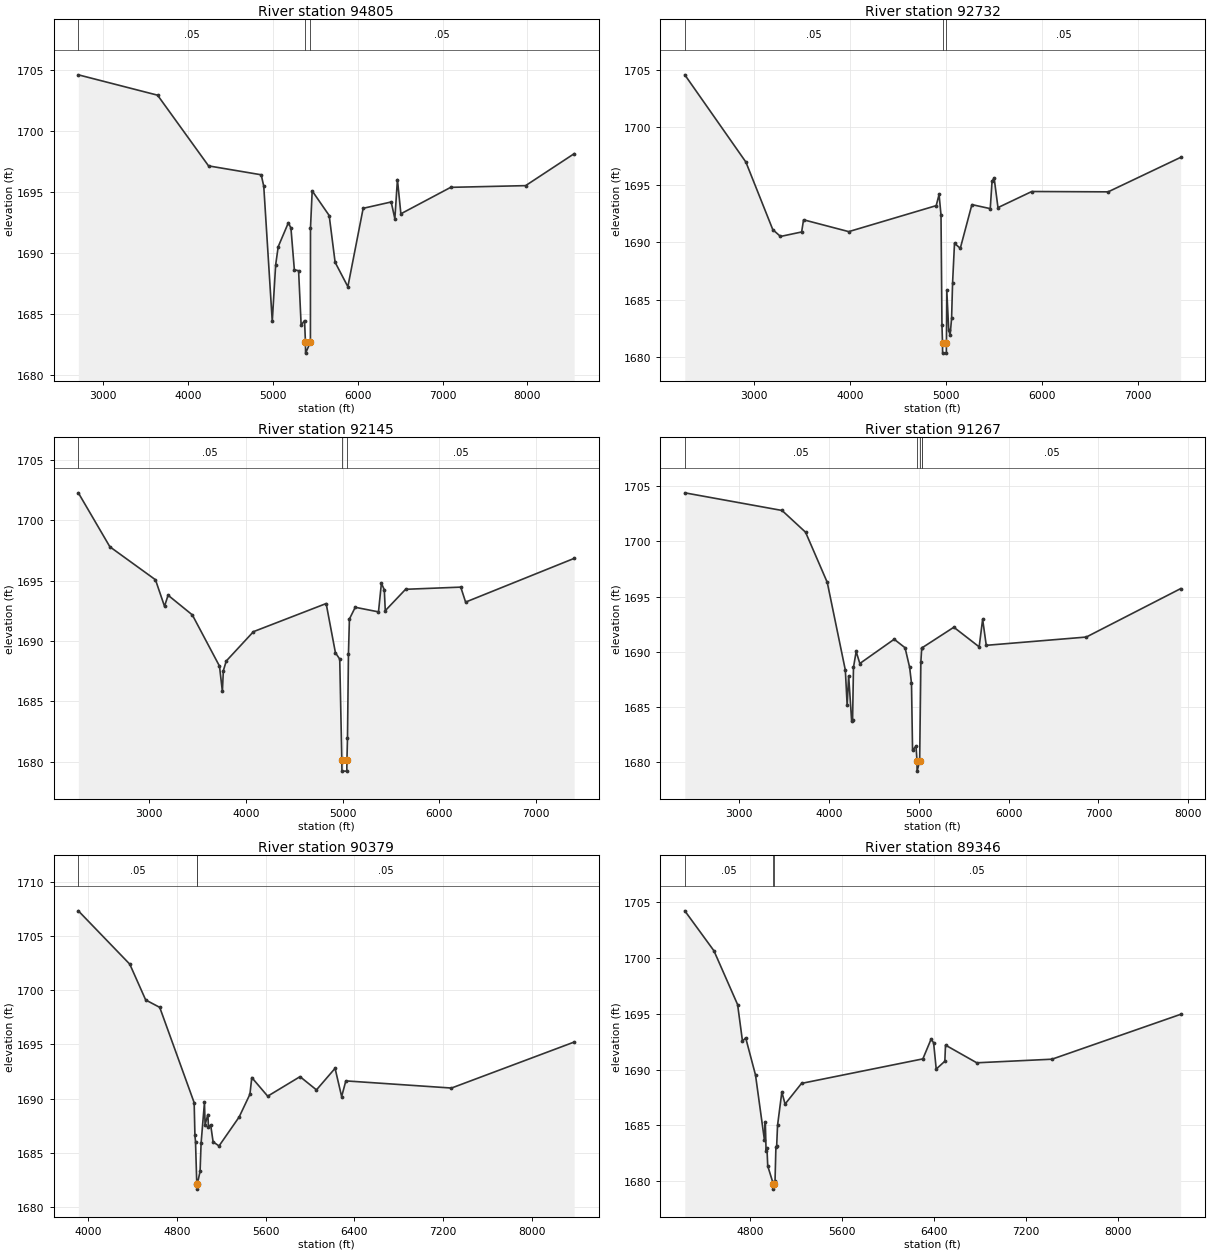
Type RM Length L Ch R = 1,94805,2073,2073,2073
BEGIN DESCRIPTION:
Mapping XS 3886a005
END DESCRIPTION:
XS GIS Cut Line= 4
      1611941.71      6881555.13      1612013.16      6884105.84
      1612049.04      6885264.99      1614151.57      6885591.13
#Sta/Elev= 30
  2711.3 1704.61  3644.5 1702.94  4244.8 1697.14  4865.0 1696.41  4895.0 1695.47
  4995.1 1684.39  5035.1 1689.02  5065.1 1690.51  5185.1 1692.48  5215.2 1692.03
  5255.2 1688.62  5305.2 1688.54  5335.2 1684.08  5375.2 1684.45  5386.0 1682.68
  5387.4 1681.78  5444.5 1682.68  5445.3 1692.05  5465.3 1695.09  5665.4 1693.07
  5735.4 1689.23  5885.5 1687.23  6065.6 1693.66  6395.7 1694.18  6438.9 1692.80
  6469.2 1696.02  6509.7 1693.21  7096.6 1695.38  7978.8 1695.52  8550.4 1698.14
#Mann=3,-1,0
  2711.3    0.05       0  5386.0    0.03       0  5444.5    0.05       0
Bank Sta=5386,5444.5
Exp/Cntr=0.3,0.1

Type RM Length L Ch R = 1,92732,587,587,587
BEGIN DESCRIPTION:
Deadman Creek 117.0
END DESCRIPTION:
XS GIS Cut Line= 3
      1608889.28      6885362.21      1611605.00      6885488.00
      1614035.13      6885764.99
#Sta/Elev= 30
  2280.9 1704.58  2917.3 1696.99  3197.6 1691.11  3277.7 1690.52  3497.9 1690.91
  3517.9 1691.97  3988.5 1690.94  4899.4 1693.20  4929.5 1694.17  4949.5 1692.39
  4959.5 1682.82  4965.1 1681.27  4966.2 1680.37  5005.2 1680.37  5006.2 1681.27
  5009.6 1685.86  5029.7 1682.40  5044.3 1681.93  5059.9 1683.40  5070.0 1686.46
  5090.1 1689.92  5150.5 1689.49  5271.3 1693.29  5462.5 1692.94  5481.4 1695.33
  5502.8 1695.61  5543.0 1693.03  5895.3 1694.43  6690.4 1694.40  7445.4 1697.40
#Mann=3,-1,0
  2280.9    0.05       0  4965.1    0.05       0  5006.2    0.05       0
Bank Sta=4965.1,5006.2
Exp/Cntr=0.3,0.1

Type RM Length L Ch R = 1,92145,878,878,878
BEGIN DESCRIPTION:
Deadman Creek 116.0
END DESCRIPTION:
XS GIS Cut Line= 4
      1608979.60      6886223.32      1611705.00      6886038.00
      1612115.65      6886016.19      1614096.60      6885966.07
#Sta/Elev= 30
  2268.2 1702.27  2594.3 1697.80  3065.4 1695.07  3159.0 1692.87  3195.7 1693.79
  3446.3 1692.16  3727.0 1687.92  3757.0 1685.83  3767.0 1687.54  3797.1 1688.34
  4077.8 1690.77  4829.5 1693.10  4925.5 1689.02  4969.8 1688.50  4991.5 1680.12
  4992.8 1679.22  5043.0 1679.22  5044.3 1680.12  5050.0 1681.93  5060.0 1688.95
  5070.0 1691.82  5130.1 1692.79  5370.4 1692.41  5400.5 1694.78  5430.5 1694.24
  5440.5 1692.51  5650.5 1694.28  6220.7 1694.46  6270.7 1693.22  7392.7 1696.84
#Mann=3,-1,0
  2268.2    0.05       0  4991.5    0.05       0  5044.3    0.05       0
Bank Sta=4991.5,5044.3
Exp/Cntr=0.3,0.1

Type RM Length L Ch R = 1,91267,888,888,888
BEGIN DESCRIPTION:
Deadman Creek 114.0
END DESCRIPTION:
XS GIS Cut Line= 4
      1608830.03      6886463.00      1611257.37      6886744.16
      1611604.59      6886820.55      1614296.13      6886432.89
#Sta/Elev= 30
  2396.3 1704.41  3478.5 1702.81  3740.2 1700.84  3981.8 1696.29  4183.1 1688.33
  4203.3 1685.14  4219.9 1687.82  4253.6 1683.68  4263.7 1683.84  4273.7 1688.58
  4303.6 1690.02  4344.2 1688.93  4726.7 1691.13  4847.7 1690.36  4898.9 1688.57
  4919.4 1687.13  4931.1 1681.07  4969.8 1681.44  4980.9 1680.07  4981.6 1679.17
  5010.2 1680.07  5023.8 1689.10  5033.1 1690.33  5038.3 1690.36  5390.7 1692.22
  5672.5 1690.44  5711.1 1692.94  5751.5 1690.58  6864.8 1691.33  7914.7 1695.72
#Mann=5,-1,0
  2396.3    0.05       0  4980.9    0.05       0  5010.2    0.05       0
  5033.1    0.12       0  5038.3    0.05       0
Bank Sta=4980.9,5010.2
Exp/Cntr=0.3,0.1

Type RM Length L Ch R = 1,90379,1033,1033,1033
BEGIN DESCRIPTION:
Mapping XS 98c7c1f3
END DESCRIPTION:
XS GIS Cut Line= 6
      1609993.76      6887715.14      1610789.73      6887400.28
      1611393.90      6887178.06      1611907.82      6886929.55
      1612215.11      6886755.98      1614239.92      6886510.58
#Sta/Elev= 30
  3914.6 1707.31  4377.8 1702.39  4521.0 1699.09  4647.2 1698.41  4957.3 1689.62
  4964.1 1686.60  4969.4 1686.04  4980.8 1682.15  4981.3 1681.65  4986.8 1682.15
  5010.6 1683.30  5019.7 1685.90  5050.1 1689.64  5055.5 1687.59  5080.6 1688.53
  5085.9 1687.40  5105.8 1687.57  5127.8 1686.01  5181.1 1685.63  5362.2 1688.30
  5459.3 1690.40  5475.9 1691.94  5619.2 1690.22  5910.3 1692.02  6058.2 1690.80
  6225.7 1692.79  6284.9 1690.18  6322.5 1691.63  7273.6 1690.97  8377.9 1695.21
#Mann=3,-1,0
  3914.6    0.05       0  4980.8    0.05       0  4986.8    0.05       0
Bank Sta=4980.8,4986.8
Exp/Cntr=0.3,0.1

Type RM Length L Ch R = 1,89346,801,801,801
BEGIN DESCRIPTION:
Mapping XS 953c1ba7
END DESCRIPTION:
XS GIS Cut Line= 5
      1611083.20      6888643.93      1611643.07      6888010.27
      1611967.14      6886931.32      1612235.99      6886785.22
      1614258.08      6886578.01
#Sta/Elev= 30
  4235.4 1704.18  4488.7 1700.61  4694.5 1695.80  4737.0 1692.53  4764.8 1692.83
  4850.1 1689.51  4927.9 1683.69  4935.5 1685.30  4942.1 1682.70  4949.7 1682.99
  4956.4 1681.38  5003.7 1679.81  5004.0 1679.31  5007.7 1679.81  5019.9 1680.03
  5027.5 1683.06  5034.2 1683.18  5041.7 1685.00  5079.1 1687.99  5107.2 1686.91
  5250.4 1688.76  6305.3 1690.95  6376.5 1692.71  6398.6 1692.39  6421.3 1690.04
  6496.3 1690.74  6502.0 1692.18  6773.9 1690.60  7427.3 1690.92  8546.2 1694.93
#Mann=3,-1,0
  4235.4    0.05       0  5003.7    0.05       0  5007.7    0.05       0
Bank Sta=5003.7,5007.7
Exp/Cntr=0.3,0.1

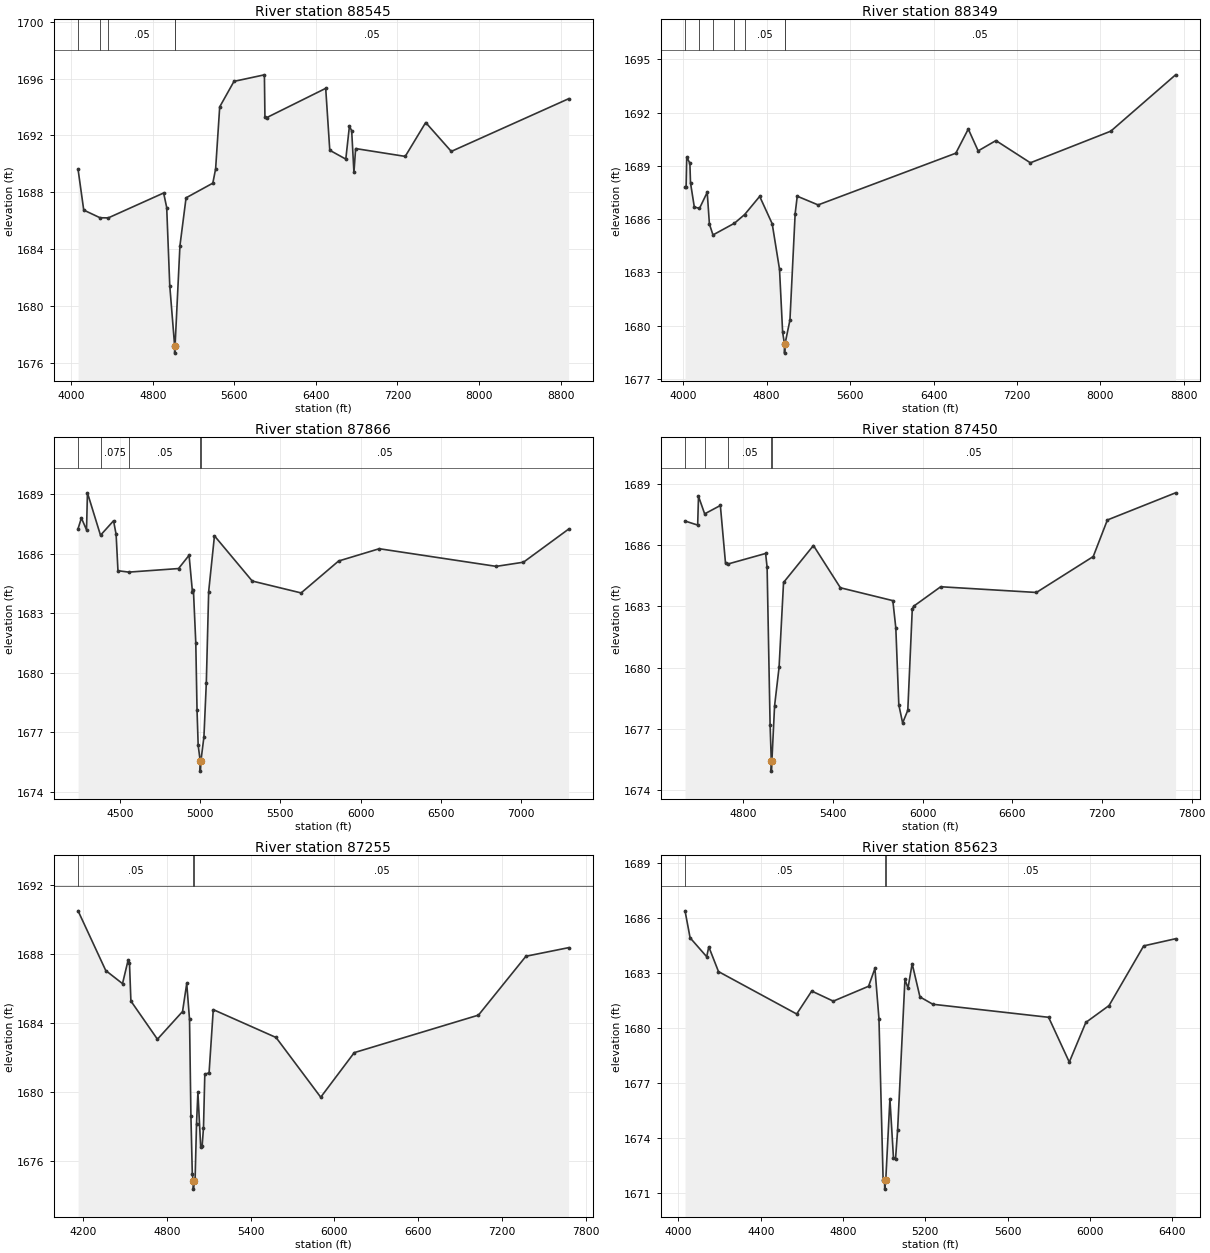
Type RM Length L Ch R = 1,88545,196,196,196
BEGIN DESCRIPTION:
Mapping XS 0fca7203
END DESCRIPTION:
XS GIS Cut Line= 6
      1611974.64      6889488.79      1612059.73      6889303.68
      1612033.69      6888188.23      1612024.76      6886948.61
      1612254.54      6886829.93      1614241.24      6886645.57
#Sta/Elev= 30
  4066.1 1689.62  4121.7 1686.76  4281.6 1686.22  4362.1 1686.21  4905.7 1687.96
  4935.7 1686.94  4965.7 1681.45  5013.7 1677.21  5014.0 1676.71  5017.7 1677.21
  5065.7 1684.26  5125.7 1687.62  5388.2 1688.65  5415.8 1689.66  5455.8 1694.01
  5595.8 1695.80  5894.4 1696.26  5899.4 1693.33  5915.8 1693.25  6495.8 1695.31
  6535.8 1690.96  6693.0 1690.34  6728.5 1692.66  6750.7 1692.33  6772.8 1689.40
  6789.4 1691.08  7276.0 1690.53  7476.9 1692.91  7727.9 1690.88  8879.1 1694.58
#Mann=5,-1,0
  4066.1    0.05       0  4281.6   0.075       0  4362.1    0.05       0
  5013.7    0.03       0  5017.7    0.05       0
Bank Sta=5013.7,5017.7
Exp/Cntr=0.3,0.1

Type RM Length L Ch R = 1,88349,483,483,483
BEGIN DESCRIPTION:
Mapping XS 9542e30f
END DESCRIPTION:
XS GIS Cut Line= 6
      1611985.02      6889500.99      1612229.01      6889342.74
      1612211.64      6888392.22      1612208.83      6888179.54
      1612214.91      6886914.03      1614195.11      6886816.70
#Sta/Elev= 30
  4017.4 1687.81  4027.7 1687.79  4033.7 1689.50  4064.0 1689.14  4069.9 1688.04
  4106.2 1686.69  4155.7 1686.60  4230.1 1687.51  4251.2 1685.72  4285.4 1685.11
  4491.2 1685.77  4589.2 1686.26  4733.0 1687.28  4853.0 1685.74  4923.1 1683.18
  4953.1 1679.63  4971.1 1678.96  4971.3 1678.46  4975.1 1678.96  5023.1 1680.32
  5073.1 1686.31  5093.1 1687.29  5293.1 1686.80  6613.1 1689.71  6732.6 1691.07
  6827.3 1689.84  6997.5 1690.42  7327.9 1689.17  8098.8 1690.95  8719.7 1694.12
#Mann=7,-1,0
  4017.4    0.05       0  4155.7   0.075       0  4285.4    0.05       0
  4491.2   0.075       0  4589.2    0.05       0  4971.1    0.05       0
  4975.1    0.05       0
Bank Sta=4971.1,4975.1
Exp/Cntr=0.3,0.1

Type RM Length L Ch R = 1,87866,416,416,416
BEGIN DESCRIPTION:
Mapping XS 47806a55
END DESCRIPTION:
XS GIS Cut Line= 5
      1611986.75      6889520.09      1612294.11      6889351.42
      1612697.76      6888761.14      1613159.31      6888223.88
      1614446.81      6888219.19
#Sta/Elev= 30
  4237.1 1687.27  4257.9 1687.81  4289.9 1687.21  4295.6 1689.08  4377.1 1686.94
  4458.6 1687.67  4474.6 1686.98  4486.1 1685.15  4554.0 1685.08  4864.1 1685.26
  4929.9 1685.93  4950.8 1684.09  4956.9 1684.20  4971.8 1681.51  4979.5 1678.13
  4986.7 1676.34  4999.6 1675.54  4999.9 1675.04  5003.6 1675.54  5022.6 1676.77
  5037.5 1679.49  5052.2 1684.10  5088.3 1686.91  5324.1 1684.63  5629.2 1684.03
  5863.0 1685.64  6116.8 1686.26  6846.8 1685.37  7016.8 1685.58  7298.6 1687.25
#Mann=5,-1,0
  4237.1    0.05       0  4377.1   0.075       0  4554.0    0.05       0
  4999.6    0.05       0  5003.6    0.05       0
Bank Sta=4999.6,5003.6
Exp/Cntr=0.3,0.1

Type RM Length L Ch R = 1,87450,195,195,195
BEGIN DESCRIPTION:
Mapping XS 72b7c0d3
END DESCRIPTION:
XS GIS Cut Line= 5
      1611997.20      6889528.75      1612346.53      6889377.42
      1612922.39      6889385.42      1613190.32      6889361.42
      1615245.53      6889286.32
#Sta/Elev= 30
  4410.3 1687.18  4494.9 1686.98  4500.4 1688.39  4541.7 1687.53  4646.7 1687.94
  4681.1 1685.12  4700.3 1685.08  4949.5 1685.59  4959.5 1684.91  4979.5 1677.19
  4987.5 1675.43  4987.7 1674.93  4991.5 1675.43  5009.5 1678.13  5039.5 1680.01
  5069.5 1684.17  5269.5 1685.98  5449.9 1683.91  5800.7 1683.28  5820.7 1681.94
  5840.7 1678.18  5866.2 1677.29  5900.8 1677.91  5930.8 1682.87  5940.8 1683.01
  6120.9 1683.96  6761.3 1683.68  7141.6 1685.44  7236.2 1687.23  7692.5 1688.56
#Mann=5,-1,0
  4410.3    0.05       0  4541.7   0.075       0  4700.3    0.05       0
  4987.5    0.05       0  4991.5    0.05       0
Bank Sta=4987.5,4991.5
Exp/Cntr=0.3,0.1

Type RM Length L Ch R = 1,87255,1632,1632,1632
BEGIN DESCRIPTION:
Mapping XS ca57eee8
END DESCRIPTION:
XS GIS Cut Line= 4
      1611786.65      6889577.37      1612834.41      6889549.38
      1613298.30      6889549.38      1615300.93      6889525.04
#Sta/Elev= 30
  4163.0 1690.51  4361.4 1687.04  4481.5 1686.28  4521.5 1687.64  4531.5 1687.46
  4541.5 1685.27  4731.6 1683.05  4911.6 1684.66  4941.6 1686.29  4961.6 1684.20
  4971.6 1678.59  4981.6 1675.19  4988.9 1674.84  4989.3 1674.34  4994.3 1674.84
  5001.6 1674.92  5011.7 1678.14  5021.7 1679.96  5041.7 1676.79  5051.7 1676.82
  5061.7 1677.91  5071.1 1681.01  5101.7 1681.10  5131.7 1684.77  5581.7 1683.15
  5901.7 1679.68  6141.8 1682.27  7031.8 1684.45  7371.8 1687.87  7677.8 1688.37
#Mann=3,-1,0
  4163.0    0.05       0  4988.9    0.03       0  4994.3    0.05       0
Bank Sta=4988.9,4994.3
Exp/Cntr=0.3,0.1

Type RM Length L Ch R = 1,85623,1054,1054,1054
BEGIN DESCRIPTION:
Mapping XS db46728b
END DESCRIPTION:
XS GIS Cut Line= 4
      1612150.54      6890361.18      1613286.30      6890513.15
      1613650.21      6890549.14      1614519.21      6890635.08
#Sta/Elev= 30
  4032.1 1686.38  4056.8 1684.91  4137.5 1683.88  4147.6 1684.42  4194.8 1683.07
  4575.0 1680.76  4648.0 1682.01  4752.9 1681.46  4924.4 1682.27  4955.2 1683.24
  4974.9 1680.51  4995.1 1671.74  5002.4 1671.72  5002.8 1671.22  5008.0 1671.72
  5028.2 1676.13  5045.5 1672.91  5055.6 1672.88  5065.7 1674.46  5101.2 1682.64
  5116.1 1682.17  5136.3 1683.50  5174.2 1681.69  5237.0 1681.29  5799.7 1680.58
  5900.2 1678.14  5980.6 1680.30  6093.5 1681.22  6261.9 1684.47  6416.9 1684.86
#Mann=3,-1,0
  4032.1    0.05       0  5002.4    0.05       0  5008.0    0.05       0
Bank Sta=5002.4,5008
Exp/Cntr=0.3,0.1

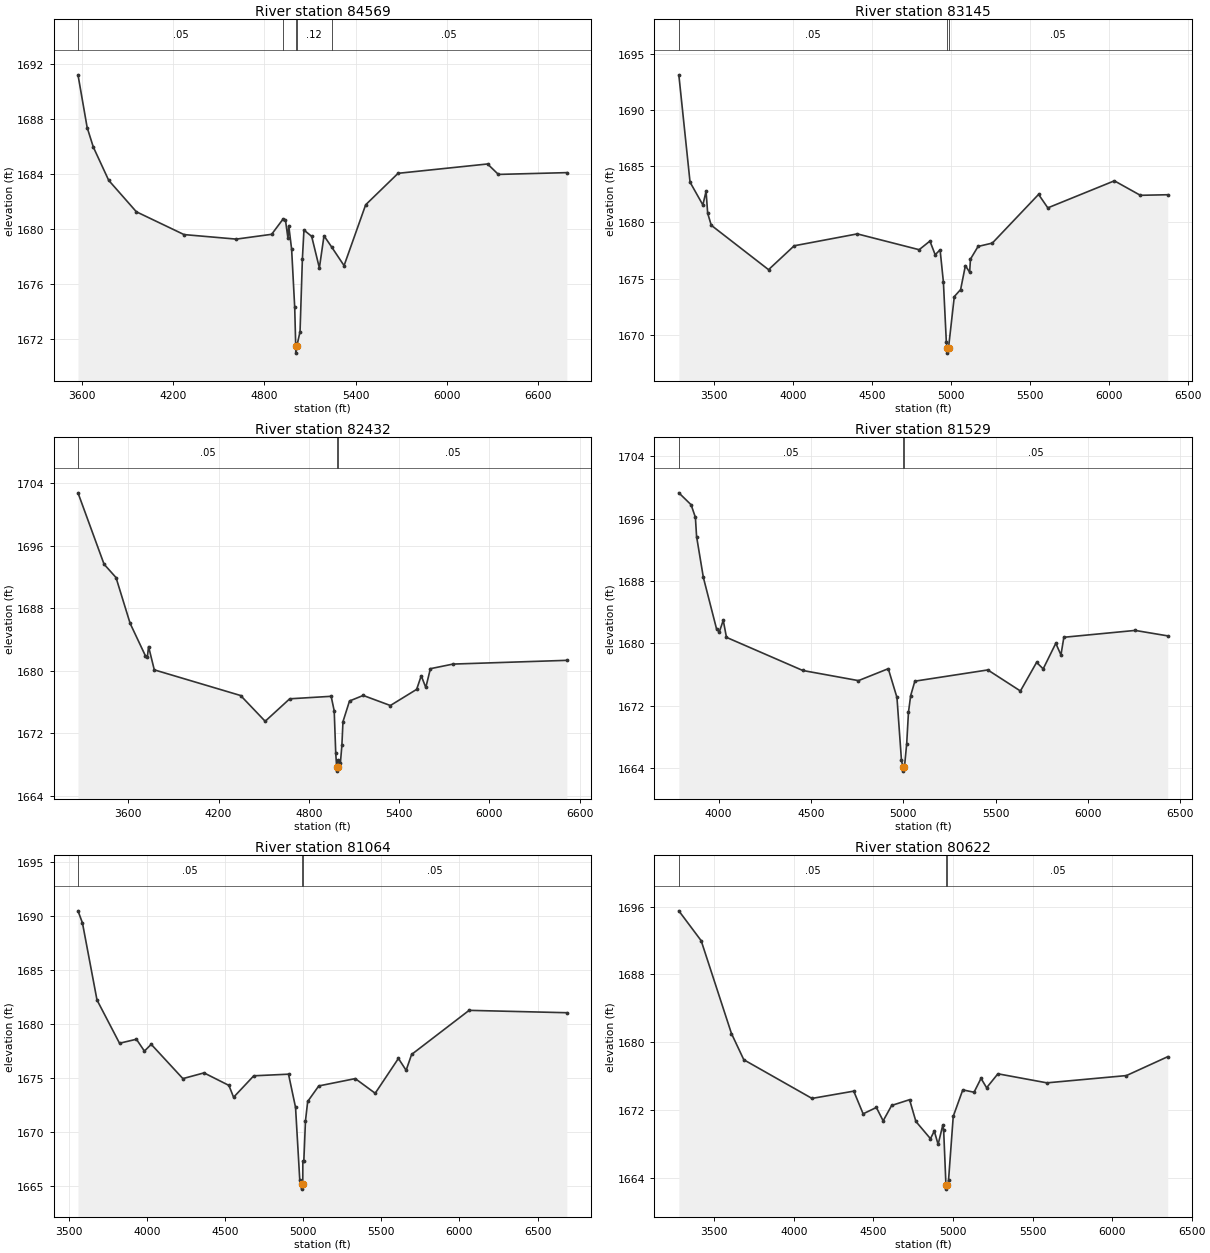
Type RM Length L Ch R = 1,84569,1424,1424,1424
BEGIN DESCRIPTION:
Deadman Creek 101.0
END DESCRIPTION:
XS GIS Cut Line= 3
      1612145.23      6891573.61      1613589.67      6891372.22
      1615318.87      6891087.49
#Sta/Elev= 30
  3576.5 1691.22  3636.8 1687.38  3677.2 1685.96  3778.2 1683.54  3959.9 1681.25
  4272.9 1679.59  4616.2 1679.26  4848.5 1679.61  4924.0 1680.73  4939.3 1680.64
  4955.7 1679.31  4960.7 1680.24  4979.7 1678.52  4999.9 1674.29  5006.6 1671.46
  5007.1 1670.96  5013.5 1671.46  5034.9 1672.52  5050.4 1677.83  5060.6 1679.92
  5111.3 1679.46  5161.9 1677.16  5192.3 1679.50  5241.7 1678.70  5324.1 1677.33
  5466.0 1681.76  5678.8 1684.05  6266.6 1684.73  6337.5 1683.97  6787.4 1684.10
#Mann=5,-1,0
  3576.5    0.05       0  4924.0    0.12       0  5006.6    0.07       0
  5013.5    0.12       0  5241.7    0.05       0
Bank Sta=5006.6,5013.5
Exp/Cntr=0.3,0.1

Type RM Length L Ch R = 1,83145,713,713,713
BEGIN DESCRIPTION:
Deadman Creek 100.0
END DESCRIPTION:
XS GIS Cut Line= 3
      1612605.01      6892488.00      1614256.33      6892198.61
      1615671.52      6892066.81
#Sta/Elev= 30
  3276.6 1693.16  3347.7 1683.59  3428.9 1681.56  3449.2 1682.78  3459.3 1680.83
  3482.0 1679.75  3845.1 1675.79  4007.6 1677.92  4407.4 1678.98  4799.4 1677.57
  4867.6 1678.34  4901.0 1677.12  4932.1 1677.56  4953.1 1674.68  4971.8 1669.30
  4978.0 1668.85  4978.5 1668.35  4985.7 1668.85  5022.1 1673.39  5062.2 1674.02
  5092.4 1676.15  5119.4 1675.56  5124.5 1676.73  5172.7 1677.86  5263.1 1678.16
  5556.1 1682.50  5614.6 1681.30  6036.4 1683.71  6201.0 1682.42  6374.4 1682.47
#Mann=3,-1,0
  3276.6    0.05       0  4978.0    0.05       0  4985.7    0.05       0
Bank Sta=4978,4985.7
Exp/Cntr=0.3,0.1

Type RM Length L Ch R = 1,82432,903,903,903
BEGIN DESCRIPTION:
Deadman Creek 99.0
END DESCRIPTION:
XS GIS Cut Line= 3
      1612554.97      6893233.33      1614284.11      6892886.11
      1615749.38      6892636.11
#Sta/Elev= 30
  3265.6 1702.80  3439.0 1693.65  3518.4 1691.94  3612.4 1686.06  3714.4 1681.89
  3727.1 1681.81  3734.8 1683.09  3772.9 1680.11  4346.8 1676.82  4510.0 1673.52
  4673.2 1676.40  4948.6 1676.72  4969.0 1674.86  4979.2 1669.40  4985.4 1667.63
  4985.9 1667.13  4993.1 1667.63  4994.4 1668.59  5009.8 1668.11  5020.0 1670.42
  5027.2 1673.47  5070.7 1676.12  5161.8 1676.83  5342.3 1675.54  5517.1 1677.61
  5547.5 1679.35  5577.9 1677.85  5608.4 1680.26  5758.4 1680.85  6515.7 1681.33
#Mann=3,-1,0
  3265.6    0.05       0  4985.4    0.05       0  4993.1    0.05       0
Bank Sta=4985.4,4993.1
Exp/Cntr=0.3,0.1

Type RM Length L Ch R = 1,81529,465,465,465
BEGIN DESCRIPTION:
Deadman Creek 97.0
END DESCRIPTION:
XS GIS Cut Line= 3
      1612971.65      6894038.87      1614105.00      6893588.00
      1615338.99      6892872.62
#Sta/Elev= 30
  3785.0 1699.30  3851.4 1697.77  3874.7 1696.15  3881.1 1693.69  3917.8 1688.44
  3989.0 1681.86  4003.9 1681.44  4025.4 1682.95  4042.9 1680.76  4455.9 1676.51
  4757.2 1675.21  4918.6 1676.74  4965.6 1673.05  4989.9 1665.04  4998.0 1664.10
  4998.5 1663.60  5006.1 1664.10  5018.4 1667.13  5027.9 1671.15  5039.9 1673.29
  5062.5 1675.14  5457.3 1676.58  5633.8 1673.88  5721.4 1677.55  5757.1 1676.72
  5825.4 1680.00  5853.2 1678.50  5869.0 1680.77  6254.9 1681.65  6431.1 1680.95
#Mann=3,-1,0
  3785.0    0.05       0  4998.0    0.05       0  5006.1    0.05       0
Bank Sta=4998,5006.1
Exp/Cntr=0.3,0.1

Type RM Length L Ch R = 1,81064,442,442,442
BEGIN DESCRIPTION:
Deadman Creek 96.0
END DESCRIPTION:
XS GIS Cut Line= 3
      1613155.00      6894738.00      1614355.00      6893938.00
      1615596.63      6892795.81
#Sta/Elev= 30
  3558.2 1690.48  3586.7 1689.36  3679.9 1682.21  3824.1 1678.20  3932.3 1678.57
  3983.4 1677.47  4026.9 1678.10  4229.7 1674.92  4364.9 1675.45  4524.2 1674.29
  4554.2 1673.19  4683.4 1675.18  4905.8 1675.33  4950.8 1672.25  4977.9 1665.49
  4988.9 1665.17  4989.4 1664.67  4997.0 1665.17  4997.4 1667.28  5003.8 1667.28
  5014.3 1671.00  5028.5 1672.80  5099.4 1674.24  5333.0 1674.92  5460.6 1673.56
  5609.2 1676.79  5658.6 1675.69  5693.7 1677.16  6061.8 1681.25  6687.5 1681.03
#Mann=3,-1,0
  3558.2    0.05       0  4988.9    0.05       0  4997.0    0.05       0
Bank Sta=4988.9,4997
Exp/Cntr=0.3,0.1

Type RM Length L Ch R = 1,80622,868,868,868
BEGIN DESCRIPTION:
Deadman Creek 95.0
END DESCRIPTION:
XS GIS Cut Line= 3
      1613054.96      6894888.02      1614655.00      6894238.00
      1615728.54      6893427.79
#Sta/Elev= 30
  3277.5 1695.52  3417.9 1691.99  3608.2 1681.02  3685.8 1677.92  4114.3 1673.35
  4376.6 1674.21  4435.6 1671.53  4518.8 1672.28  4561.4 1670.70  4614.9 1672.52
  4727.4 1673.20  4767.1 1670.63  4858.6 1668.59  4882.7 1669.49  4906.8 1667.92
  4936.2 1670.20  4941.6 1669.61  4955.9 1663.13  4956.4 1662.63  4964.8 1663.13
  4972.2 1663.66  5001.8 1671.23  5061.8 1674.36  5132.6 1674.08  5176.3 1675.72
  5211.6 1674.61  5282.4 1676.26  5590.5 1675.19  6090.0 1676.05  6349.5 1678.28
#Mann=3,-1,0
  3277.5    0.05       0  4955.9    0.03       0  4964.8    0.05       0
Bank Sta=4955.9,4964.8
Exp/Cntr=0.3,0.1