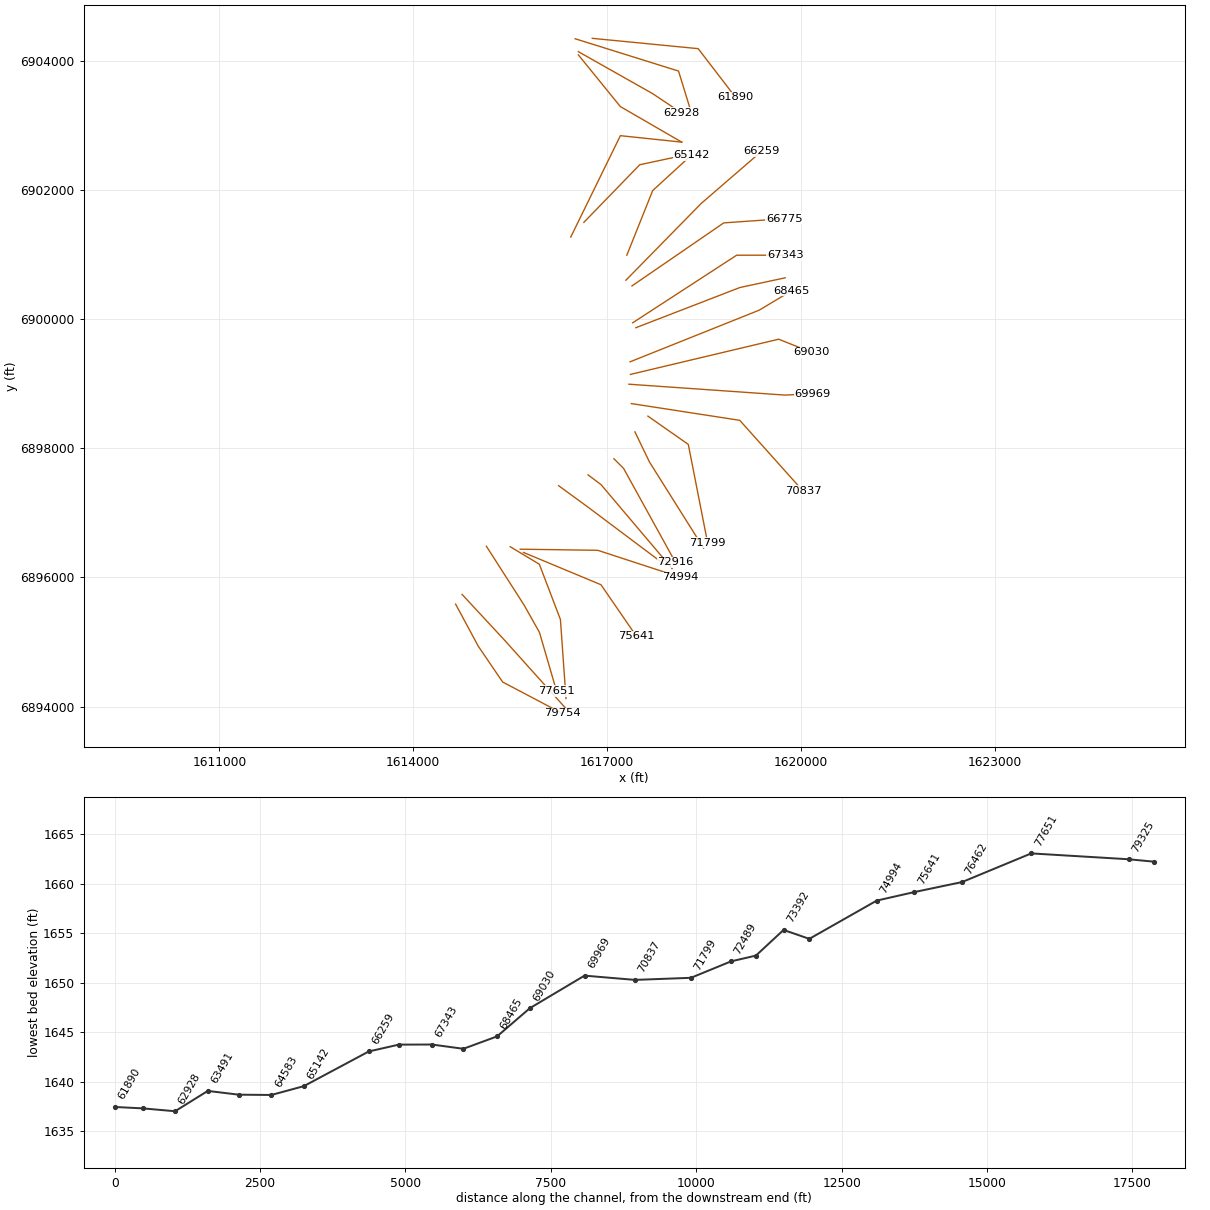
HEC-RAS study Deadman Creek.prj: Deadman Creek Base Level Engineering

--- Deadman Creek.g01 (geometry) --- (continued)

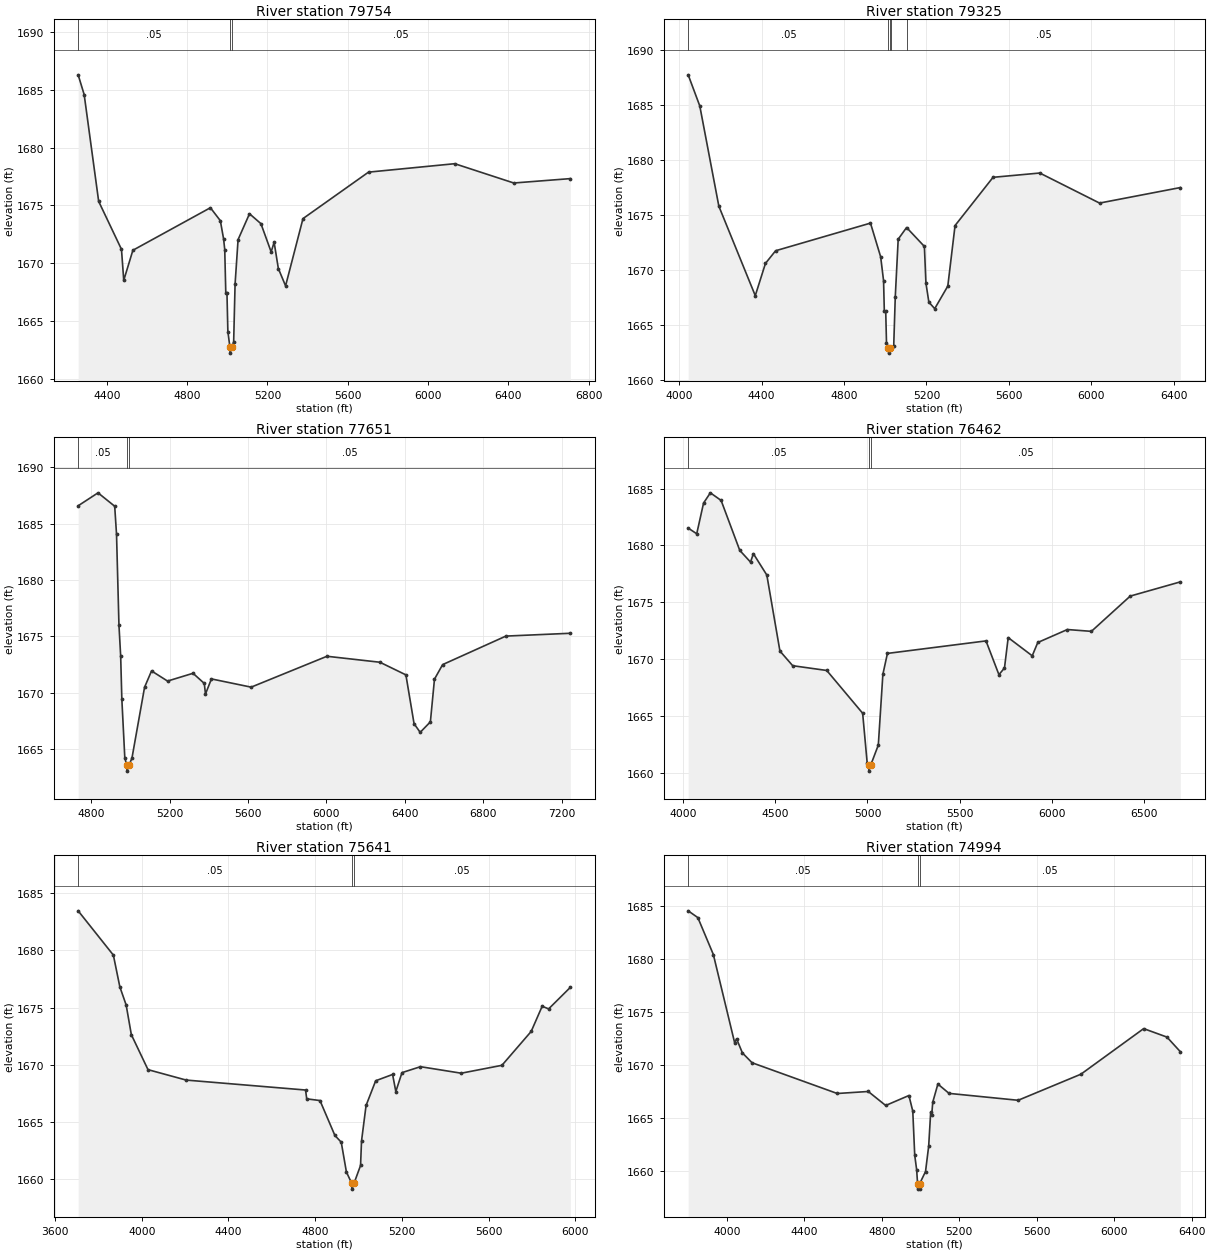
Type RM Length L Ch R = 1,79754,429,429,429
BEGIN DESCRIPTION:
Deadman Creek 94.0
END DESCRIPTION:
XS GIS Cut Line= 4
      1614655.01      6895587.97      1615005.00      6894938.00
      1615382.53      6894382.93      1616304.08      6893897.04
#Sta/Elev= 30
  4257.0 1686.29  4287.0 1684.58  4359.2 1675.34  4472.8 1671.19  4484.1 1668.51
  4529.6 1671.11  4915.7 1674.79  4965.2 1673.67  4981.4 1672.09  4987.1 1671.17
  4992.4 1667.38  4998.2 1667.38  5002.7 1664.08  5013.1 1662.71  5013.6 1662.21
  5022.1 1662.71  5031.5 1663.17  5038.6 1668.18  5053.5 1672.03  5110.4 1674.27
  5167.4 1673.41  5218.2 1670.97  5233.1 1671.80  5254.1 1669.53  5290.1 1668.03
  5376.8 1673.85  5703.2 1677.87  6132.6 1678.60  6426.7 1676.93  6708.3 1677.31
#Mann=3,-1,0
  4257.0    0.05       0  5013.1    0.05       0  5022.1    0.05       0
Bank Sta=5013.1,5022.1
Exp/Cntr=0.3,0.1

Type RM Length L Ch R = 1,79325,1674,1674,1674
BEGIN DESCRIPTION:
Deadman Creek 93.0
END DESCRIPTION:
XS GIS Cut Line= 3
      1614755.02      6895737.98      1615405.00      6895038.00
      1616362.44      6893971.82
#Sta/Elev= 30
  4043.7 1687.73  4100.1 1684.90  4192.5 1675.80  4369.3 1667.67  4418.7 1670.60
  4468.0 1671.75  4928.3 1674.26  4977.7 1671.20  4991.8 1669.03  4995.5 1666.24
  5002.3 1666.24  5006.0 1663.41  5015.7 1662.95  5016.2 1662.45  5024.7 1662.95
  5027.1 1662.97  5041.1 1663.12  5048.6 1667.55  5062.8 1672.80  5103.5 1673.86
  5189.9 1672.14  5197.4 1668.81  5211.6 1667.08  5240.0 1666.49  5303.5 1668.54
  5338.7 1674.04  5523.1 1678.42  5749.8 1678.81  6039.8 1676.08  6431.9 1677.49
#Mann=5,-1,0
  4043.7    0.05       0  5015.7    0.05       0  5024.7    0.05       0
  5027.1    0.12       0  5103.5    0.05       0
Bank Sta=5015.7,5024.7
Exp/Cntr=0.3,0.1

Type RM Length L Ch R = 1,77651,1189,1189,1189
BEGIN DESCRIPTION:
Mapping XS 0e1e119b
END DESCRIPTION:
XS GIS Cut Line= 4
      1615131.33      6896483.34      1615714.67      6895573.61
      1615952.52      6895150.99      1616217.41      6894242.26
#Sta/Elev= 30
  4732.8 1686.58  4834.2 1687.73  4919.4 1686.54  4928.7 1684.04  4941.1 1675.98
  4949.8 1673.26  4955.8 1669.43  4971.0 1664.21  4981.3 1663.54  4981.8 1663.04
  4991.0 1663.54  5007.3 1664.18  5071.8 1670.48  5107.4 1671.93  5189.1 1671.03
  5319.2 1671.72  5376.7 1670.82  5382.7 1669.88  5413.1 1671.22  5615.9 1670.49
  6002.8 1673.23  6273.1 1672.70  6405.7 1671.58  6447.4 1667.25  6478.6 1666.48
  6530.7 1667.41  6551.6 1671.20  6593.2 1672.49  6916.1 1675.02  7245.0 1675.27
#Mann=3,-1,0
  4732.8    0.05       0  4981.3    0.05       0  4991.0    0.05       0
Bank Sta=4981.3,4991
Exp/Cntr=0.3,0.1

Type RM Length L Ch R = 1,76462,821,821,821
BEGIN DESCRIPTION:
Mapping XS 7cb89e1a
END DESCRIPTION:
XS GIS Cut Line= 4
      1615499.36      6896476.41      1615950.78      6896205.56
      1616277.21      6895349.78      1616363.46      6894126.97
#Sta/Elev= 30
  4027.9 1681.52  4074.3 1681.02  4111.3 1683.72  4148.2 1684.62  4206.5 1683.95
  4307.6 1679.56  4365.9 1678.53  4381.4 1679.27  4454.3 1677.39  4525.3 1670.71
  4594.5 1669.42  4779.2 1669.00  4973.8 1665.24  4998.5 1660.84  5007.0 1660.65
  5007.5 1660.15  5016.8 1660.65  5058.7 1662.44  5083.4 1668.66  5108.1 1670.50
  5642.5 1671.60  5712.6 1668.63  5742.7 1669.22  5762.8 1671.89  5893.1 1670.29
  5923.2 1671.46  6083.6 1672.60  6213.9 1672.44  6424.4 1675.54  6696.1 1676.79
#Mann=3,-1,0
  4027.9    0.05       0  5007.0    0.05       0  5016.8    0.05       0
Bank Sta=5007,5016.8
Exp/Cntr=0.3,0.1

Type RM Length L Ch R = 1,75641,647,647,647
BEGIN DESCRIPTION:
Deadman Creek 91.0
END DESCRIPTION:
XS GIS Cut Line= 3
      1615705.02      6896387.99      1616905.00      6895888.00
      1617455.00      6895088.01
#Sta/Elev= 30
  3706.6 1683.46  3869.1 1679.59  3898.9 1676.82  3928.1 1675.23  3952.0 1672.64
  4028.9 1669.58  4204.9 1668.67  4755.8 1667.80  4761.2 1667.03  4822.4 1666.88
  4891.2 1663.83  4920.5 1663.24  4944.3 1660.64  4968.9 1659.64  4969.4 1659.14
  4979.3 1659.64  5009.6 1661.21  5014.0 1663.34  5035.0 1666.45  5079.4 1668.61
  5157.4 1669.16  5172.3 1667.67  5200.7 1669.32  5286.0 1669.84  5474.1 1669.27
  5661.9 1669.96  5796.8 1672.92  5847.5 1675.12  5877.3 1674.89  5977.4 1676.77
#Mann=3,-1,0
  3706.6    0.05       0  4968.9    0.05       0  4979.3    0.05       0
Bank Sta=4968.9,4979.3
Exp/Cntr=0.3,0.1

Type RM Length L Ch R = 1,74994,1159,1159,1159
BEGIN DESCRIPTION:
Deadman Creek 90.0
END DESCRIPTION:
XS GIS Cut Line= 3
      1615655.03      6896438.00      1616855.11      6896420.83
      1618130.65      6896004.39
#Sta/Elev= 30
  3799.8 1684.53  3849.8 1683.89  3929.8 1680.41  4039.8 1672.09  4049.8 1672.46
  4079.8 1671.13  4129.8 1670.20  4569.8 1667.30  4729.9 1667.49  4819.9 1666.17
  4939.9 1667.11  4959.9 1665.63  4969.9 1661.48  4979.9 1660.10  4984.7 1658.78
  4985.2 1658.28  4994.6 1658.28  4995.1 1658.78  5025.7 1659.94  5042.0 1662.34
  5052.3 1665.52  5057.6 1665.26  5063.0 1666.48  5089.5 1668.19  5147.2 1667.31
  5504.0 1666.66  5828.2 1669.12  6152.4 1673.42  6272.7 1672.62  6341.8 1671.24
#Mann=3,-1,0
  3799.8    0.05       0  4984.7    0.05       0  4995.1    0.05       0
Bank Sta=4984.7,4995.1
Exp/Cntr=0.3,0.1

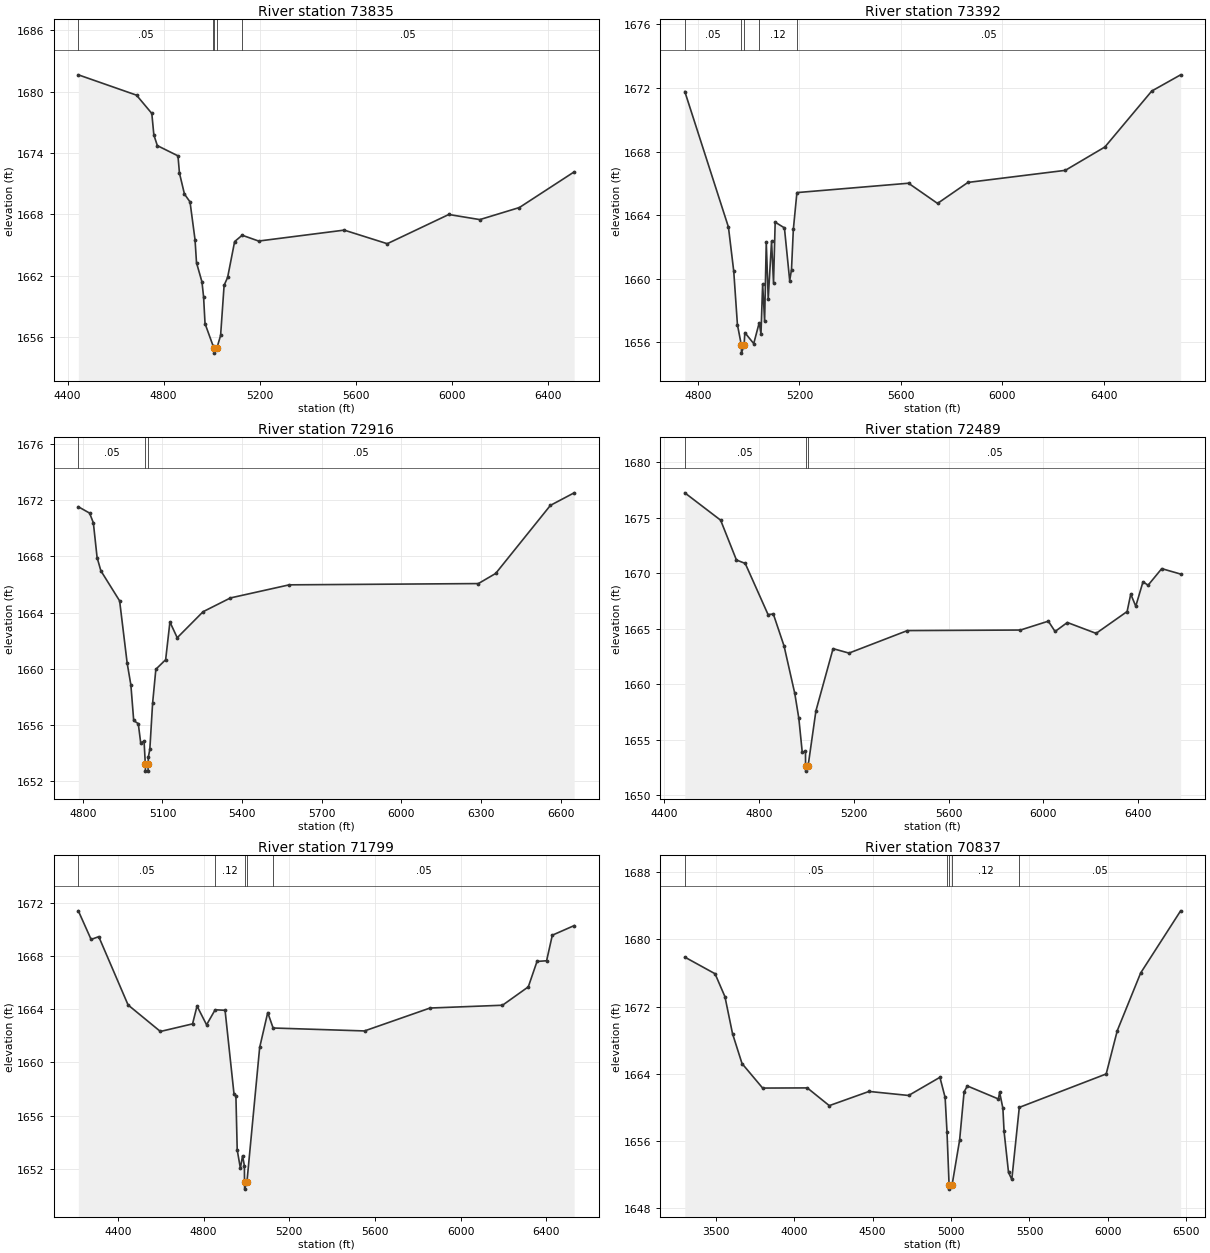
Type RM Length L Ch R = 1,73835,443,443,443
BEGIN DESCRIPTION:
Deadman Creek 89.0
END DESCRIPTION:
XS GIS Cut Line= 3
      1616249.40      6897420.82      1616705.00      6897088.00
      1617904.99      6896188.01
#Sta/Elev= 30
  4444.8 1681.66  4687.0 1679.67  4750.7 1677.88  4759.2 1675.78  4773.7 1674.73
  4859.6 1673.73  4865.8 1672.04  4886.6 1669.99  4909.8 1669.22  4930.6 1665.53
  4936.8 1663.27  4959.5 1661.39  4966.2 1659.94  4972.3 1657.31  5006.1 1655.11
  5011.0 1654.92  5011.5 1654.42  5021.6 1654.92  5037.1 1656.15  5051.7 1661.06
  5066.3 1661.83  5095.5 1665.34  5126.9 1665.96  5195.5 1665.39  5551.7 1666.46
  5730.9 1665.13  5987.1 1667.99  6116.3 1667.49  6280.9 1668.67  6509.0 1672.16
#Mann=5,-1,0
  4444.8    0.05       0  5006.1    0.12       0  5011.0    0.05       0
  5021.6    0.12       0  5126.9    0.05       0
Bank Sta=5011,5021.6
Exp/Cntr=0.3,0.1

Type RM Length L Ch R = 1,73392,476,476,476
BEGIN DESCRIPTION:
Deadman Creek 88.0
END DESCRIPTION:
XS GIS Cut Line= 3
      1616704.96      6897588.03      1616905.00      6897438.00
      1618005.01      6896137.99
#Sta/Elev= 30
  4748.7 1671.78  4920.6 1663.25  4941.5 1660.47  4956.0 1657.11  4971.5 1655.82
  4972.0 1655.32  4982.2 1655.82  4985.2 1656.61  5020.2 1655.92  5041.8 1657.23
  5048.8 1656.53  5055.3 1659.68  5063.1 1657.34  5069.6 1662.30  5077.3 1658.74
  5090.4 1662.35  5098.2 1659.74  5104.7 1663.56  5141.1 1663.20  5161.9 1659.88
  5169.0 1660.58  5176.2 1663.10  5190.3 1665.42  5629.9 1666.01  5744.2 1664.74
  5863.9 1666.06  6247.4 1666.82  6403.4 1668.29  6588.0 1671.81  6701.7 1672.83
#Mann=5,-1,0
  4748.7    0.05       0  4971.5    0.05       0  4982.2    0.05       0
  5041.8    0.12       0  5190.3    0.05       0
Bank Sta=4971.5,4982.2
Exp/Cntr=0.3,0.1

Type RM Length L Ch R = 1,72916,427,427,427
BEGIN DESCRIPTION:
Deadman Creek 87.0
END DESCRIPTION:
XS GIS Cut Line= 3
      1617104.99      6897838.01      1617255.00      6897688.00
      1618055.00      6896237.99
#Sta/Elev= 30
  4783.0 1671.52  4825.4 1671.07  4839.6 1670.38  4853.7 1667.91  4867.9 1666.97
  4938.6 1664.83  4966.9 1660.42  4981.0 1658.85  4991.6 1656.33  5008.9 1656.10
  5018.0 1654.74  5030.7 1654.86  5035.4 1653.23  5035.9 1652.73  5045.7 1652.73
  5046.2 1653.23  5046.7 1653.72  5052.4 1654.28  5062.8 1657.54  5075.1 1659.97
  5112.0 1660.65  5128.1 1663.33  5155.6 1662.21  5253.0 1664.06  5356.2 1665.04
  5577.6 1665.97  6290.2 1666.06  6355.5 1666.78  6561.8 1671.62  6651.2 1672.51
#Mann=3,-1,0
  4783.0    0.05       0  5035.4    0.05       0  5046.2    0.05       0
Bank Sta=5035.4,5046.2
Exp/Cntr=0.3,0.1

Type RM Length L Ch R = 1,72489,690,690,690
BEGIN DESCRIPTION:
Deadman Creek 86.0
END DESCRIPTION:
XS GIS Cut Line= 3
      1617429.95      6898254.16      1617655.00      6897788.00
      1618492.44      6896455.55
#Sta/Elev= 30
  4487.3 1677.26  4638.5 1674.79  4705.1 1671.20  4742.2 1670.89  4838.4 1666.28
  4860.8 1666.32  4906.0 1663.44  4951.2 1659.16  4968.3 1656.91  4982.7 1653.85
  4996.4 1653.94  4996.7 1652.65  4997.2 1652.15  5007.6 1652.65  5040.4 1657.59
  5112.7 1663.20  5179.8 1662.80  5426.0 1664.83  5903.0 1664.88  6020.7 1665.68
  6049.1 1664.75  6100.9 1665.56  6222.2 1664.58  6353.0 1666.55  6368.3 1668.12
  6389.5 1667.03  6420.1 1669.24  6441.3 1668.92  6499.0 1670.42  6578.7 1669.93
#Mann=3,-1,0
  4487.3    0.05       0  4996.7    0.05       0  5007.6    0.05       0
Bank Sta=4996.7,5007.6
Exp/Cntr=0.3,0.1

Type RM Length L Ch R = 1,71799,962,962,962
BEGIN DESCRIPTION:
Deadman Creek 85.0
END DESCRIPTION:
XS GIS Cut Line= 3
      1617631.32      6898497.23      1618256.33      6898059.72
      1618555.00      6896537.98
#Sta/Elev= 30
  4215.4 1671.39  4275.0 1669.24  4310.7 1669.45  4447.6 1664.32  4598.3 1662.33
  4748.4 1662.90  4769.3 1664.24  4813.8 1662.83  4853.9 1663.96  4900.1 1663.92
  4942.0 1657.61  4950.7 1657.49  4956.8 1653.43  4971.6 1652.06  4981.8 1653.00
  4990.3 1652.24  4990.9 1650.99  4991.4 1650.49  5001.9 1650.99  5061.6 1661.13
  5099.2 1663.75  5124.3 1662.59  5550.8 1662.37  5856.5 1664.09  6194.7 1664.30
  6315.1 1665.68  6355.8 1667.59  6400.5 1667.64  6427.2 1669.56  6529.1 1670.28
#Mann=5,-1,0
  4215.4    0.05       0  4853.9    0.12       0  4990.9    0.07       0
  5001.9    0.12       0  5124.3    0.05       0
Bank Sta=4990.9,5001.9
Exp/Cntr=0.3,0.1

Type RM Length L Ch R = 1,70837,868,868,868
BEGIN DESCRIPTION:
Mapping XS d820e1d5
END DESCRIPTION:
XS GIS Cut Line= 3
      1617374.38      6898691.67      1619052.58      6898432.46
      1620028.91      6897341.83
#Sta/Elev= 30
  3301.9 1677.90  3494.8 1675.92  3557.9 1673.19  3606.1 1668.80  3666.8 1665.23
  3798.3 1662.31  4083.0 1662.33  4223.3 1660.22  4476.9 1661.91  4729.2 1661.43
  4928.8 1663.59  4962.0 1661.19  4973.9 1657.12  4987.3 1650.78  4987.8 1650.28
  5006.5 1650.78  5054.5 1656.13  5083.0 1661.87  5103.9 1662.56  5302.0 1661.01
  5309.5 1661.82  5330.4 1659.90  5337.9 1657.15  5366.3 1652.27  5387.2 1651.43
  5435.0 1660.01  5989.1 1663.99  6060.1 1669.16  6208.9 1676.01  6463.8 1683.41
#Mann=5,-1,0
  3301.9    0.05       0  4973.9    0.12       0  4987.3    0.07       0
  5006.5    0.12       0  5435.0    0.05       0
Bank Sta=4987.3,5006.5
Exp/Cntr=0.3,0.1

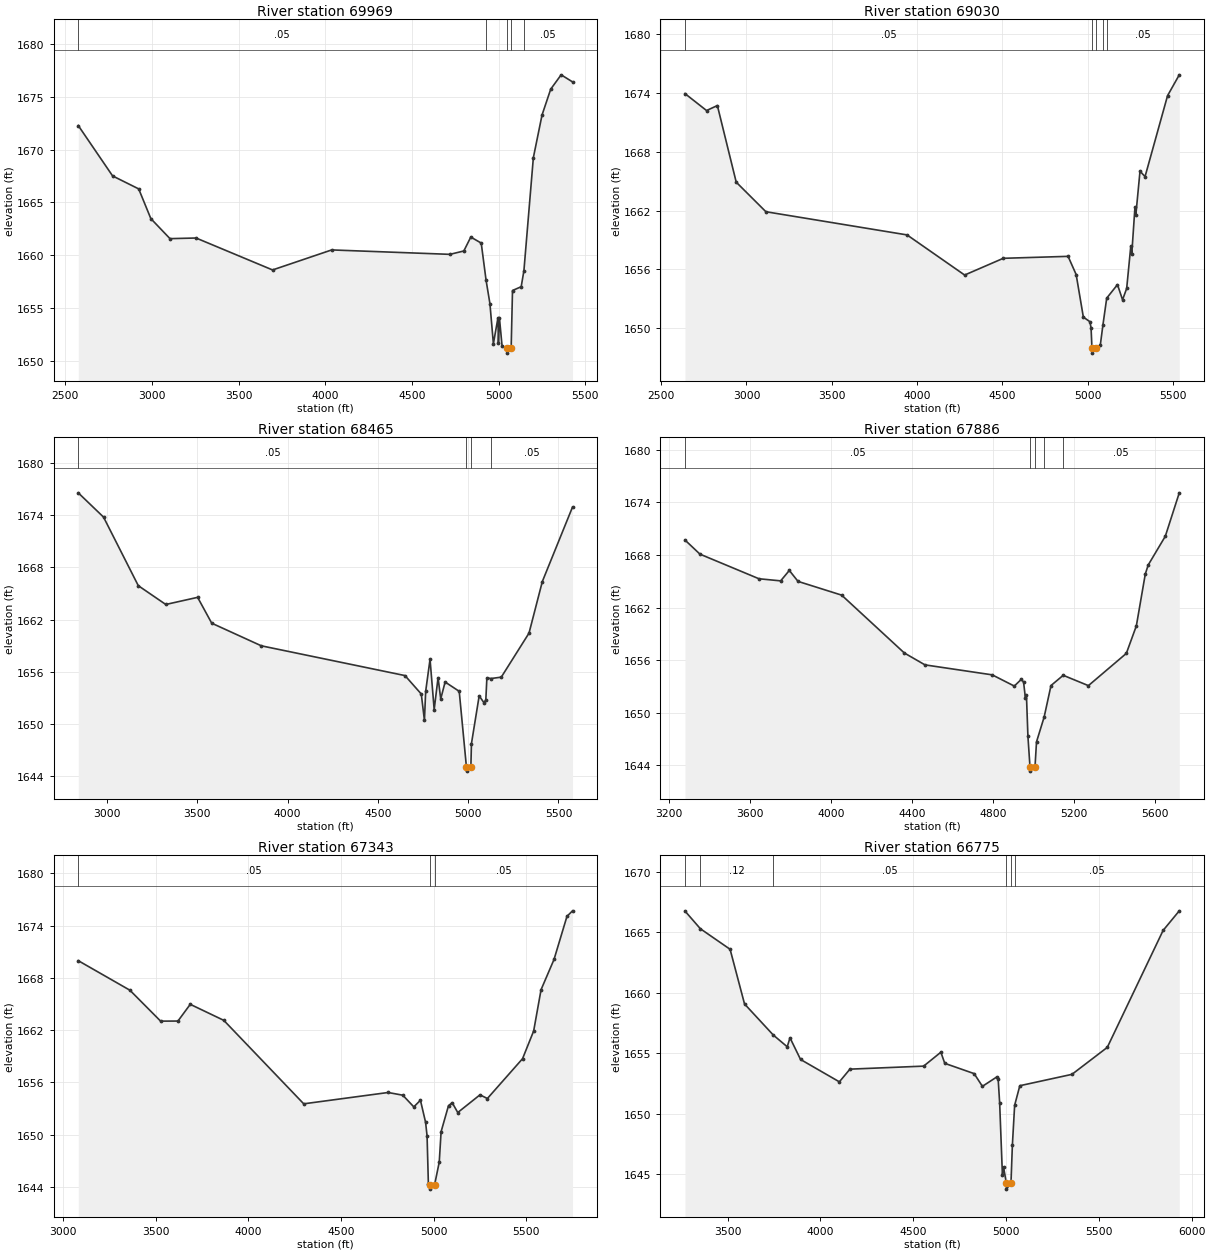
Type RM Length L Ch R = 1,69969,939,939,939
BEGIN DESCRIPTION:
Deadman Creek 84.0
END DESCRIPTION:
XS GIS Cut Line= 3
      1617337.47      6898991.51      1619755.49      6898822.80
      1620180.58      6898845.65
#Sta/Elev= 30
  2576.1 1672.30  2774.1 1667.52  2924.5 1666.29  2994.6 1663.47  3104.9 1661.57
  3255.3 1661.63  3696.3 1658.60  4037.2 1660.50  4718.8 1660.08  4799.0 1660.40
  4839.1 1661.72  4899.3 1661.15  4927.2 1657.63  4949.4 1655.41  4969.4 1651.60
  4995.8 1654.06  4998.5 1651.63  5004.2 1654.06  5019.5 1651.38  5047.2 1651.21
  5047.7 1650.71  5071.9 1651.21  5079.6 1656.65  5129.7 1657.01  5145.4 1658.53
  5199.8 1669.25  5249.9 1673.30  5299.9 1675.75  5360.0 1677.11  5425.7 1676.44
#Mann=5,-1,0
  2576.1    0.05       0  4927.2    0.12       0  5047.2    0.07       0
  5071.9    0.12       0  5145.4    0.05       0
Bank Sta=5047.2,5071.9
Exp/Cntr=0.3,0.1

Type RM Length L Ch R = 1,69030,565,565,565
BEGIN DESCRIPTION:
Deadman Creek 83.0
END DESCRIPTION:
XS GIS Cut Line= 3
      1617360.45      6899143.05      1619655.00      6899688.00
      1620155.01      6899488.00
#Sta/Elev= 30
  2640.0 1673.95  2766.3 1672.22  2829.7 1672.73  2940.2 1664.90  3114.1 1661.88
  3941.5 1659.51  4278.9 1655.41  4505.4 1657.12  4885.2 1657.32  4932.5 1655.46
  4974.7 1651.11  5013.2 1650.64  5019.9 1650.00  5025.1 1647.93  5025.6 1647.43
  5049.8 1647.93  5073.8 1648.21  5089.4 1650.31  5111.6 1653.05  5174.7 1654.43
  5204.4 1652.88  5228.6 1654.04  5252.8 1658.37  5258.2 1657.51  5277.1 1662.34
  5282.4 1661.57  5306.7 1666.02  5336.3 1665.47  5468.2 1673.74  5536.9 1675.87
#Mann=5,-1,0
  2640.0    0.05       0  5025.1    0.03       0  5049.8    0.05       0
  5089.4    0.12       0  5111.6    0.05       0
Bank Sta=5025.1,5049.8
Exp/Cntr=0.3,0.1

Type RM Length L Ch R = 1,68465,579,579,579
BEGIN DESCRIPTION:
Deadman Creek 82.0
END DESCRIPTION:
XS GIS Cut Line= 3
      1617354.99      6899337.99      1619355.00      6900138.00
      1619855.02      6900438.01
#Sta/Elev= 30
  2840.8 1676.56  2980.8 1673.77  3173.3 1665.89  3325.5 1663.73  3501.8 1664.55
  3579.9 1661.58  3854.6 1658.98  4650.2 1655.56  4740.4 1653.44  4757.9 1650.41
  4764.7 1653.75  4788.9 1657.43  4811.8 1651.65  4833.3 1655.32  4848.1 1652.88
  4872.4 1654.82  4950.5 1653.75  4990.3 1645.08  4990.8 1644.58  5015.0 1645.08
  5018.2 1647.74  5061.0 1653.23  5088.2 1652.42  5097.9 1652.80  5103.7 1655.30
  5126.3 1655.22  5183.4 1655.38  5337.0 1660.44  5410.8 1666.37  5578.0 1674.93
#Mann=4,-1,0
  2840.8    0.05       0  4990.3    0.05       0  5015.0    0.05       0
  5126.3    0.05       0
Bank Sta=4990.3,5015
Exp/Cntr=0.3,0.1

Type RM Length L Ch R = 1,67886,543,543,543
BEGIN DESCRIPTION:
Deadman Creek 81.0
END DESCRIPTION:
XS GIS Cut Line= 3
      1617443.87      6899865.29      1619055.00      6900488.00
      1619755.03      6900638.01
#Sta/Elev= 30
  3277.5 1669.71  3351.4 1668.10  3643.2 1665.29  3750.4 1665.05  3793.1 1666.24
  3836.2 1664.99  4051.9 1663.42  4361.5 1656.82  4463.6 1655.46  4796.2 1654.32
  4905.3 1653.04  4940.6 1653.83  4951.2 1653.47  4959.9 1651.72  4965.2 1652.01
  4972.6 1647.29  4982.7 1643.83  4983.2 1643.33  5007.6 1643.83  5015.0 1646.67
  5052.7 1649.50  5086.6 1653.10  5147.0 1654.27  5271.5 1653.09  5459.0 1656.77
  5508.5 1659.91  5552.8 1665.84  5567.3 1666.87  5651.6 1670.14  5720.7 1675.10
#Mann=5,-1,0
  3277.5    0.05       0  4982.7    0.05       0  5007.6    0.05       0
  5052.7    0.12       0  5147.0    0.05       0
Bank Sta=4982.7,5007.6
Exp/Cntr=0.3,0.1

Type RM Length L Ch R = 1,67343,568,568,568
BEGIN DESCRIPTION:
Deadman Creek 80.0
END DESCRIPTION:
XS GIS Cut Line= 3
      1617395.20      6899941.66      1619005.00      6900988.00
      1619755.03      6900988.00
#Sta/Elev= 30
  3080.8 1669.98  3359.7 1666.59  3525.7 1663.04  3619.3 1663.05  3685.8 1664.97
  3867.0 1663.13  4298.7 1653.55  4754.7 1654.85  4833.8 1654.54  4893.4 1653.20
  4929.2 1653.96  4957.0 1651.43  4965.0 1649.88  4972.1 1644.40  4980.7 1644.26
  4981.2 1643.76  5005.7 1644.26  5030.8 1646.86  5040.8 1650.35  5080.8 1653.34
  5100.8 1653.68  5130.8 1652.55  5250.8 1654.58  5290.8 1654.16  5480.8 1658.73
  5540.8 1661.91  5580.8 1666.65  5650.8 1670.12  5720.8 1675.07  5750.8 1675.70
#Mann=3,-1,0
  3080.8    0.05       0  4980.7    0.05       0  5005.7    0.05       0
Bank Sta=4980.7,5005.7
Exp/Cntr=0.3,0.1

Type RM Length L Ch R = 1,66775,516,516,516
BEGIN DESCRIPTION:
Deadman Creek 79.0
END DESCRIPTION:
XS GIS Cut Line= 3
      1617384.33      6900512.38      1618805.00      6901488.00
      1619741.88      6901553.89
#Sta/Elev= 30
  3271.0 1666.74  3353.7 1665.28  3513.9 1663.58  3591.7 1659.06  3746.6 1656.49
  3821.7 1655.52  3836.6 1656.26  3893.5 1654.47  4102.6 1652.62  4159.4 1653.67
  4556.6 1653.92  4649.3 1655.07  4670.3 1654.15  4828.6 1653.30  4873.1 1652.25
  4951.1 1653.03  4958.0 1652.84  4966.0 1650.87  4980.9 1644.90  4987.0 1645.57
  5002.0 1644.25  5002.5 1643.75  5027.0 1644.25  5034.5 1647.38  5046.7 1650.68
  5074.6 1652.30  5355.5 1653.24  5545.8 1655.47  5846.5 1665.14  5933.6 1666.76
#Mann=6,-1,0
  3271.0    0.05       0  3353.7    0.12       0  3746.6    0.05       0
  5002.0    0.05       0  5027.0    0.05       0  5046.7    0.05       0
Bank Sta=5002,5027
Exp/Cntr=0.3,0.1

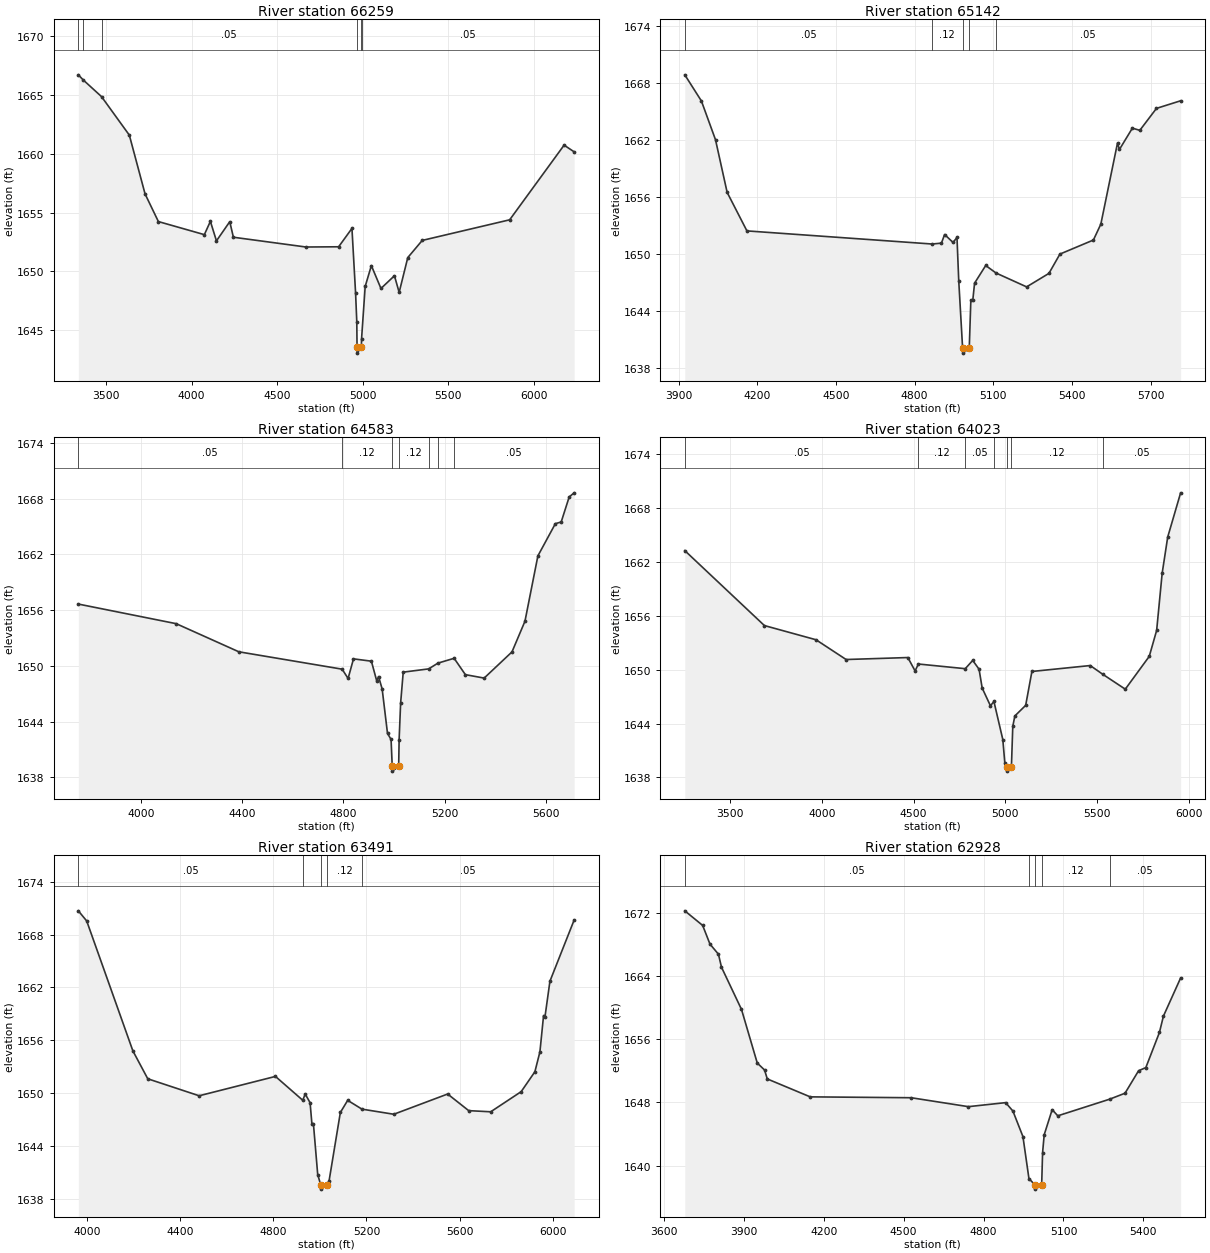
Type RM Length L Ch R = 1,66259,1117,1117,1117
BEGIN DESCRIPTION:
Deadman Creek 78.0
END DESCRIPTION:
XS GIS Cut Line= 3
      1617290.53      6900600.87      1618455.00      6901788.00
      1619389.52      6902595.69
#Sta/Elev= 30
  3337.7 1666.69  3366.6 1666.25  3473.2 1664.84  3635.8 1661.57  3727.7 1656.58
  3805.6 1654.23  4074.3 1653.12  4109.6 1654.25  4145.0 1652.59  4222.8 1654.22
  4244.0 1652.90  4668.2 1652.07  4859.2 1652.09  4937.0 1653.65  4958.2 1648.17
  4965.3 1645.72  4966.8 1643.56  4967.3 1643.06  4992.0 1643.56  4993.0 1644.23
  5014.3 1648.72  5050.5 1650.49  5106.5 1648.55  5185.4 1649.63  5212.9 1648.22
  5263.3 1651.17  5347.8 1652.63  5858.9 1654.38  6177.0 1660.72  6235.8 1660.15
#Mann=6,-1,0
  3337.7    0.05       0  3366.6    0.12       0  3473.2    0.05       0
  4966.8    0.05       0  4992.0    0.05       0  4993.0    0.05       0
Bank Sta=4966.8,4992
Exp/Cntr=0.3,0.1

Type RM Length L Ch R = 1,65142,559,559,559
BEGIN DESCRIPTION:
Deadman Creek 77.0
END DESCRIPTION:
XS GIS Cut Line= 3
      1617305.01      6900988.02      1617705.00      6901988.00
      1618304.96      6902537.97
#Sta/Elev= 30
  3923.6 1668.84  3986.9 1666.09  4040.7 1662.01  4085.1 1656.47  4160.5 1652.42
  4866.5 1651.04  4902.3 1651.13  4914.4 1652.04  4946.8 1651.20  4961.6 1651.74
  4968.3 1647.18  4983.1 1640.06  4983.6 1639.56  5008.4 1640.06  5014.5 1645.14
  5021.9 1645.13  5028.7 1646.92  5071.2 1648.78  5110.4 1647.99  5227.2 1646.53
  5312.3 1647.95  5354.2 1649.98  5481.9 1651.46  5510.2 1653.13  5573.8 1661.67
  5581.2 1660.99  5630.5 1663.23  5658.9 1663.00  5722.4 1665.31  5814.5 1666.11
#Mann=5,-1,0
  3923.6    0.05       0  4866.5    0.12       0  4983.1    0.07       0
  5008.4    0.12       0  5110.4    0.05       0
Bank Sta=4983.1,5008.4
Exp/Cntr=0.3,0.1

Type RM Length L Ch R = 1,64583,560,560,560
BEGIN DESCRIPTION:
Deadman Creek 76.0
END DESCRIPTION:
XS GIS Cut Line= 3
      1616639.91      6901496.70      1617505.00      6902388.00
      1618205.02      6902538.00
#Sta/Elev= 30
  3753.0 1656.66  4139.4 1654.55  4386.9 1651.52  4794.7 1649.65  4818.3 1648.65
  4839.6 1650.76  4910.3 1650.51  4931.4 1648.38  4938.6 1648.85  4952.8 1647.52
  4973.9 1642.73  4988.0 1642.08  4992.6 1639.17  4993.1 1638.67  5018.0 1639.17
  5019.8 1642.06  5025.8 1646.02  5036.0 1649.33  5136.4 1649.68  5173.0 1650.30
  5237.0 1650.82  5281.4 1649.06  5355.6 1648.69  5465.5 1651.51  5516.7 1654.81
  5567.8 1661.85  5636.8 1665.32  5659.8 1665.50  5691.4 1668.20  5711.0 1668.64
#Mann=7,-1,0
  3753.0    0.05       0  4794.7    0.12       0  4992.6    0.07       0
  5018.0    0.12       0  5136.4    0.05       0  5173.0    0.12       0
  5237.0    0.05       0
Bank Sta=4992.6,5018
Exp/Cntr=0.3,0.1

Type RM Length L Ch R = 1,64023,532,532,532
BEGIN DESCRIPTION:
Deadman Creek 75.0
END DESCRIPTION:
XS GIS Cut Line= 3
      1616436.91      6901268.09      1617205.00      6902838.00
      1618155.02      6902738.00
#Sta/Elev= 30
  3252.4 1663.24  3686.3 1654.90  3967.6 1653.32  4131.8 1651.12  4468.4 1651.34
  4507.8 1649.85  4525.8 1650.62  4781.2 1650.10  4822.0 1651.02  4856.6 1650.04
  4873.5 1647.95  4918.6 1645.97  4937.6 1646.45  4986.1 1642.21  4997.3 1639.55
  5007.5 1639.20  5008.0 1638.70  5033.0 1639.20  5040.4 1643.68  5051.7 1644.84
  5110.7 1646.02  5144.7 1649.79  5462.7 1650.45  5530.0 1649.49  5653.7 1647.82
  5784.4 1651.47  5824.7 1654.36  5854.8 1660.72  5885.0 1664.75  5955.4 1669.67
#Mann=7,-1,0
  3252.4    0.05       0  4525.8    0.12       0  4781.2    0.05       0
  4937.6    0.12       0  5007.5    0.07       0  5033.0    0.12       0
  5530.0    0.05       0
Bank Sta=5007.5,5033
Exp/Cntr=0.3,0.1

Type RM Length L Ch R = 1,63491,563,563,563
BEGIN DESCRIPTION:
Deadman Creek 74.0
END DESCRIPTION:
XS GIS Cut Line= 3
      1616554.99      6904088.01      1617205.00      6903288.00
      1618154.99      6902738.01
#Sta/Elev= 30
  3963.3 1670.71  3999.2 1669.56  4197.5 1654.79  4261.4 1651.62  4481.9 1649.69
  4809.5 1651.89  4926.7 1649.18  4937.3 1649.89  4958.2 1648.90  4966.1 1646.46
  4972.5 1646.51  4990.9 1640.74  5003.7 1639.58  5004.2 1639.08  5030.7 1639.58
  5039.3 1639.95  5088.1 1647.79  5119.6 1649.17  5180.9 1648.17  5317.6 1647.59
  5548.7 1649.89  5639.1 1648.00  5733.6 1647.87  5864.4 1650.16  5923.2 1652.42
  5944.8 1654.68  5960.5 1658.81  5966.3 1658.62  5987.8 1662.71  6091.8 1669.67
#Mann=5,-1,0
  3963.3    0.05       0  4926.7    0.12       0  5003.7    0.07       0
  5030.7    0.12       0  5180.9    0.05       0
Bank Sta=5003.7,5030.7
Exp/Cntr=0.3,0.1

Type RM Length L Ch R = 1,62928,559,559,559
BEGIN DESCRIPTION:
Deadman Creek 73.0
END DESCRIPTION:
XS GIS Cut Line= 3
      1616555.03      6904137.98      1617705.00      6903488.00
      1618155.02      6903187.99
#Sta/Elev= 30
  3678.2 1672.26  3745.3 1670.41  3772.7 1668.05  3804.5 1666.77  3816.0 1665.12
  3891.1 1659.78  3950.3 1652.99  3977.7 1652.11  3987.9 1650.98  4149.1 1648.71
  4528.2 1648.60  4742.9 1647.47  4883.0 1647.98  4910.3 1646.91  4947.9 1643.68
  4970.4 1638.37  4993.9 1637.53  4994.3 1637.03  5018.2 1637.53  5021.7 1641.65
  5027.7 1643.91  5057.7 1647.09  5078.8 1646.31  5273.0 1648.41  5331.2 1649.17
  5382.2 1652.02  5409.3 1652.41  5460.4 1656.86  5475.4 1658.93  5540.0 1663.76
#Mann=5,-1,0
  3678.2    0.05       0  4970.4    0.12       0  4993.9    0.07       0
  5018.2    0.12       0  5273.0    0.05       0
Bank Sta=4993.9,5018.2
Exp/Cntr=0.3,0.1

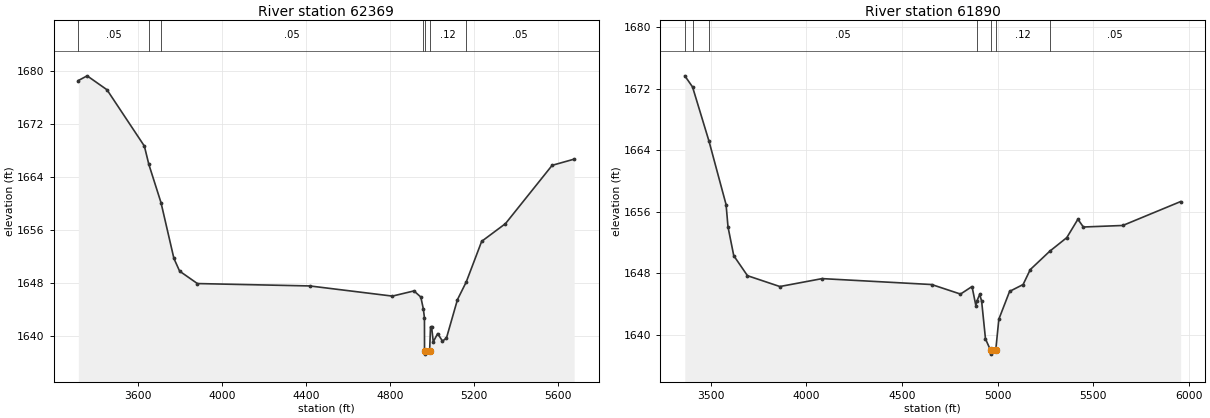
Type RM Length L Ch R = 1,62369,479,479,479
BEGIN DESCRIPTION:
Deadman Creek 72.0
END DESCRIPTION:
XS GIS Cut Line= 3
      1616505.00      6904338.00      1618105.00      6903838.00
      1618305.01      6903187.98
#Sta/Elev= 30
  3318.5 1678.53  3360.4 1679.24  3454.7 1677.14  3632.3 1668.66  3653.7 1665.89
  3711.3 1660.15  3772.7 1651.74  3799.9 1649.82  3884.3 1647.95  4418.6 1647.59
  4810.9 1646.06  4913.6 1646.84  4946.1 1645.92  4958.1 1644.14  4963.4 1642.79
  4963.8 1637.82  4964.3 1637.32  4988.1 1637.82  4992.2 1641.42  4997.4 1641.42
  5005.3 1639.17  5026.2 1640.42  5049.1 1639.28  5068.0 1639.74  5120.4 1645.54
  5162.2 1648.20  5235.4 1654.31  5348.6 1656.98  5570.3 1665.76  5674.9 1666.69
#Mann=7,-1,0
  3318.5    0.05       0  3653.7    0.12       0  3711.3    0.05       0
  4958.1    0.12       0  4963.8    0.07       0  4988.1    0.12       0
  5162.2    0.05       0
Bank Sta=4963.8,4988.1
Exp/Cntr=0.3,0.1

Type RM Length L Ch R = 1,61890,654,654,654
BEGIN DESCRIPTION:
Deadman Creek 71.0
END DESCRIPTION:
XS GIS Cut Line= 3
      1616770.26      6904344.44      1618409.11      6904184.72
      1618985.49      6903434.74
#Sta/Elev= 30
  3363.8 1673.65  3404.2 1672.21  3490.1 1665.17  3579.6 1656.91  3589.7 1654.01
  3619.8 1650.26  3691.5 1647.66  3860.9 1646.25  4081.9 1647.28  4654.6 1646.51
  4805.3 1645.27  4865.6 1646.25  4885.7 1643.77  4891.8 1644.40  4905.8 1645.24
  4915.9 1644.34  4936.0 1639.44  4962.6 1637.96  4963.1 1637.46  4989.6 1637.96
  5005.8 1642.00  5062.1 1645.62  5132.7 1646.51  5170.0 1648.45  5271.9 1650.84
  5361.1 1652.61  5419.2 1655.00  5447.7 1653.99  5653.9 1654.19  5956.3 1657.30
#Mann=7,-1,0
  3363.8    0.05       0  3404.2    0.12       0  3490.1    0.05       0
  4891.8    0.12       0  4962.6    0.07       0  4989.6    0.12       0
  5271.9    0.05       0
Bank Sta=4962.6,4989.6
Exp/Cntr=0.3,0.1