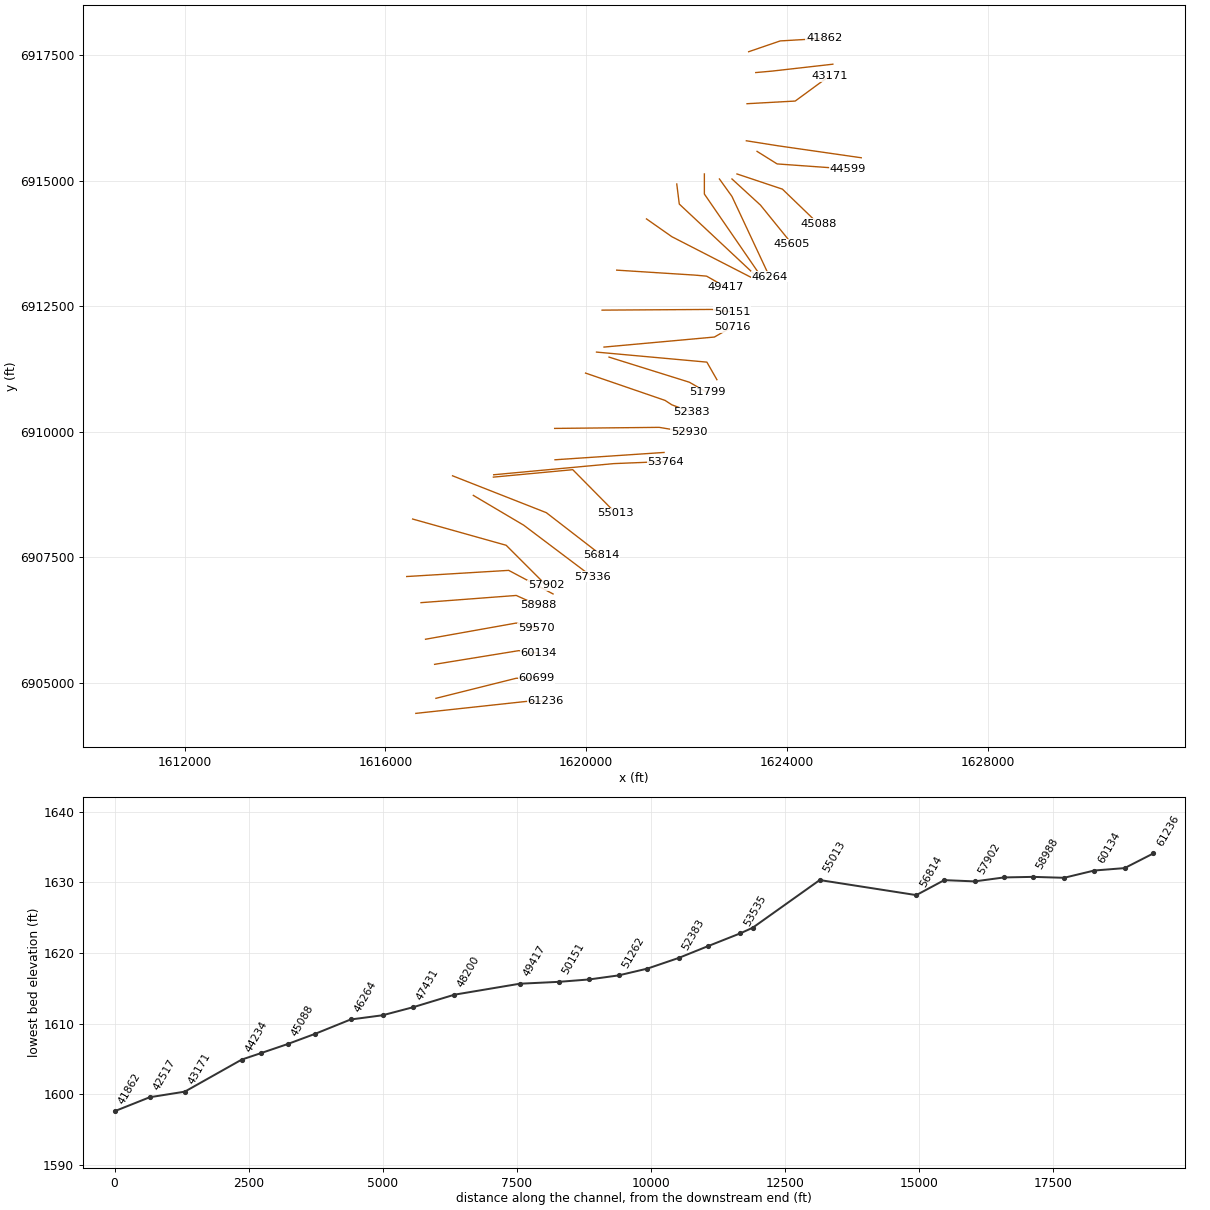
HEC-RAS study Deadman Creek.prj: Deadman Creek Base Level Engineering

--- Deadman Creek.g01 (geometry) --- (continued)

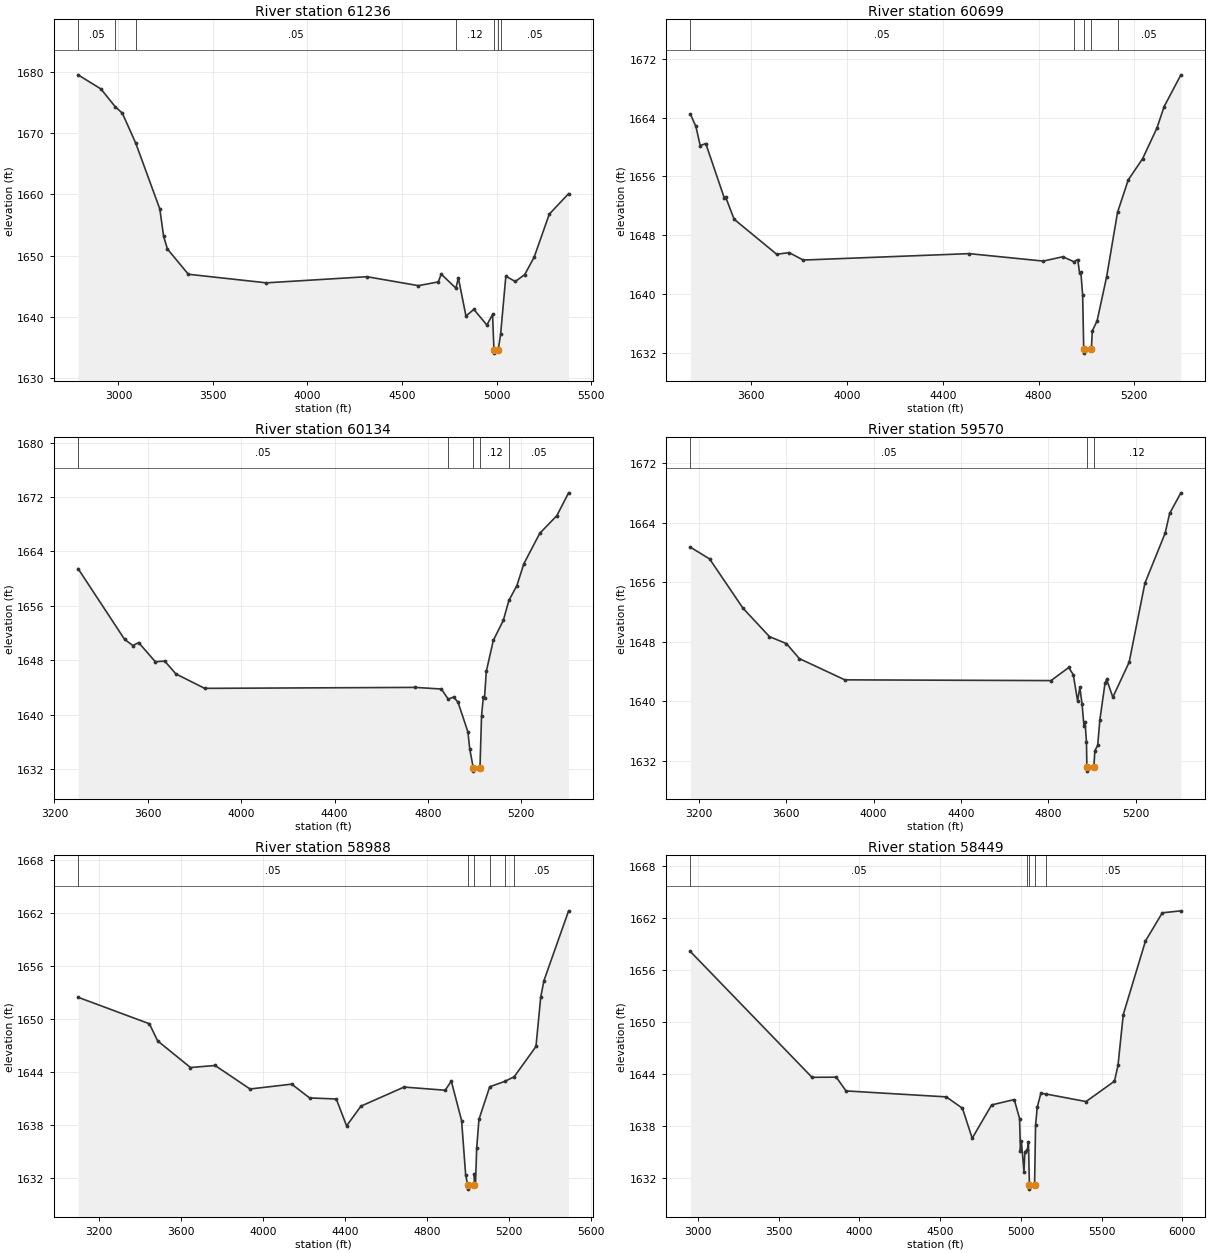
Type RM Length L Ch R = 1,61236,537,537,537
BEGIN DESCRIPTION:
Deadman Creek 70.0
END DESCRIPTION:
XS GIS Cut Line= 3
      1616605.01      6904388.00      1618805.00      6904626.23
      1619186.95      6904634.91
#Sta/Elev= 30
  2786.5 1679.50  2907.2 1677.20  2983.5 1674.28  3020.8 1673.24  3092.0 1668.32
  3219.0 1657.61  3239.1 1653.14  3259.2 1651.08  3369.9 1646.96  3782.3 1645.56
  4314.7 1646.56  4587.0 1645.10  4691.6 1645.71  4707.7 1646.98  4785.3 1644.69
  4798.2 1646.38  4838.4 1640.14  4880.1 1641.23  4949.1 1638.68  4979.2 1640.40
  4986.6 1634.59  4987.0 1634.09  5009.0 1634.59  5021.9 1637.22  5049.4 1646.64
  5099.4 1645.78  5149.4 1646.91  5199.4 1649.77  5279.4 1656.78  5381.4 1660.11
#Mann=7,-1,0
  2786.5    0.05       0  2983.5    0.12       0  3092.0    0.05       0
  4785.3    0.12       0  4986.6    0.07       0  5009.0    0.12       0
  5021.9    0.05       0
Bank Sta=4986.6,5009
Exp/Cntr=0.3,0.1

Type RM Length L Ch R = 1,60699,565,565,565
BEGIN DESCRIPTION:
Deadman Creek 69.0
END DESCRIPTION:
XS GIS Cut Line= 3
      1617005.02      6904688.00      1618605.00      6905088.00
      1619004.98      6905088.00
#Sta/Elev= 30
  3345.3 1664.47  3368.5 1662.79  3386.5 1660.19  3409.7 1660.47  3487.0 1653.08
  3492.2 1653.24  3528.2 1650.19  3706.1 1645.43  3757.6 1645.66  3816.9 1644.65
  4510.1 1645.52  4819.3 1644.51  4901.8 1645.10  4947.2 1644.42  4963.6 1644.72
  4971.3 1642.89  4976.5 1643.05  4984.2 1639.85  4988.6 1632.51  4989.1 1632.01
  5020.5 1632.51  5024.5 1635.03  5044.5 1636.40  5084.5 1642.41  5129.8 1651.12
  5174.5 1655.53  5234.5 1658.41  5294.5 1662.58  5324.5 1665.49  5394.5 1669.80
#Mann=5,-1,0
  3345.3    0.05       0  4947.2    0.12       0  4988.6    0.07       0
  5020.5    0.12       0  5129.8    0.05       0
Bank Sta=4988.6,5020.5
Exp/Cntr=0.3,0.1

Type RM Length L Ch R = 1,60134,564,564,564
BEGIN DESCRIPTION:
Deadman Creek 68.0
END DESCRIPTION:
XS GIS Cut Line= 3
      1616978.54      6905365.28      1618655.00      6905638.00
      1619054.99      6905588.00
#Sta/Elev= 30
  3301.3 1661.47  3500.3 1651.07  3536.0 1650.15  3561.1 1650.58  3632.1 1647.77
  3672.6 1647.86  3720.6 1645.97  3843.7 1643.85  4746.5 1643.99  4858.0 1643.75
  4887.3 1642.25  4910.0 1642.58  4928.9 1641.83  4971.6 1637.43  4979.5 1634.90
  4994.5 1632.17  4995.0 1631.67  5023.2 1632.17  5030.0 1639.81  5037.6 1642.56
  5042.6 1642.38  5050.2 1646.33  5080.4 1650.91  5123.3 1653.86  5147.1 1656.79
  5181.2 1658.96  5211.4 1662.20  5279.5 1666.67  5352.5 1669.26  5402.9 1672.62
#Mann=5,-1,0
  3301.3    0.05       0  4887.3    0.12       0  4994.5    0.07       0
  5023.2    0.12       0  5147.1    0.05       0
Bank Sta=4994.5,5023.2
Exp/Cntr=0.3,0.1

Type RM Length L Ch R = 1,59570,582,582,582
BEGIN DESCRIPTION:
Deadman Creek 67.0
END DESCRIPTION:
XS GIS Cut Line= 3
      1616798.03      6905865.28      1618605.00      6906188.00
      1619005.03      6906087.99
#Sta/Elev= 30
  3160.1 1660.75  3248.4 1659.16  3400.8 1652.56  3522.7 1648.72  3600.5 1647.78
  3659.4 1645.77  3868.1 1642.91  4812.8 1642.81  4894.1 1644.57  4914.9 1643.60
  4934.7 1640.07  4944.9 1641.91  4955.0 1639.69  4963.7 1636.75  4968.7 1637.27
  4975.3 1634.59  4977.2 1631.14  4977.7 1630.64  5009.1 1631.14  5013.7 1633.38
  5026.6 1634.09  5036.9 1637.57  5060.1 1642.42  5067.8 1642.96  5096.2 1640.58
  5170.9 1645.28  5243.0 1655.89  5335.8 1662.62  5356.4 1665.28  5408.0 1668.05
#Mann=3,-1,0
  3160.1    0.05       0  4977.2    0.07       0  5009.1    0.12       0
Bank Sta=4977.2,5009.1
Exp/Cntr=0.3,0.1

Type RM Length L Ch R = 1,58988,539,539,539
BEGIN DESCRIPTION:
Deadman Creek 66.0
END DESCRIPTION:
XS GIS Cut Line= 3
      1616707.76      6906594.45      1618605.00      6906738.00
      1619054.99      6906538.00
#Sta/Elev= 30
  3096.4 1652.48  3444.6 1649.48  3484.8 1647.55  3645.2 1644.53  3765.6 1644.76
  3936.0 1642.10  4139.6 1642.65  4226.9 1641.09  4357.2 1640.97  4407.5 1637.93
  4477.6 1640.16  4688.2 1642.32  4888.8 1641.96  4918.8 1642.99  4969.0 1638.53
  4989.0 1632.35  4998.7 1631.27  4999.2 1630.77  5030.7 1631.27  5031.2 1632.51
  5036.7 1631.27  5042.8 1635.44  5053.8 1638.66  5106.3 1642.35  5180.9 1642.97
  5226.0 1643.49  5332.2 1646.91  5355.4 1652.50  5371.1 1654.36  5491.5 1662.26
#Mann=6,-1,0
  3096.4    0.05       0  4998.7    0.05       0  5030.7    0.05       0
  5106.3    0.05       0  5180.9    0.12       0  5226.0    0.05       0
Bank Sta=4998.7,5030.7
Exp/Cntr=0.3,0.1

Type RM Length L Ch R = 1,58449,547,547,547
BEGIN DESCRIPTION:
Deadman Creek 65.0
END DESCRIPTION:
XS GIS Cut Line= 3
      1616423.03      6907115.28      1618455.00      6907238.00
      1619339.65      6906768.06
#Sta/Elev= 30
  2953.7 1658.15  3707.0 1643.61  3857.3 1643.63  3917.4 1642.04  4538.6 1641.35
  4638.7 1640.03  4698.8 1636.57  4819.1 1640.42  4959.3 1641.04  4992.2 1638.85
  4997.5 1635.13  5003.2 1636.24  5019.5 1632.72  5025.2 1635.01  5039.8 1635.23
  5047.2 1636.08  5053.1 1631.19  5053.6 1630.69  5085.1 1631.19  5091.3 1638.09
  5101.8 1640.17  5123.8 1641.75  5153.6 1641.69  5403.9 1640.81  5579.7 1643.16
  5601.7 1644.99  5634.3 1650.86  5771.9 1659.37  5876.1 1662.62  5991.1 1662.85
#Mann=5,-1,0
  2953.7    0.05       0  5039.8    0.12       0  5053.1    0.05       0
  5085.1    0.12       0  5153.6    0.05       0
Bank Sta=5053.1,5085.1
Exp/Cntr=0.3,0.1

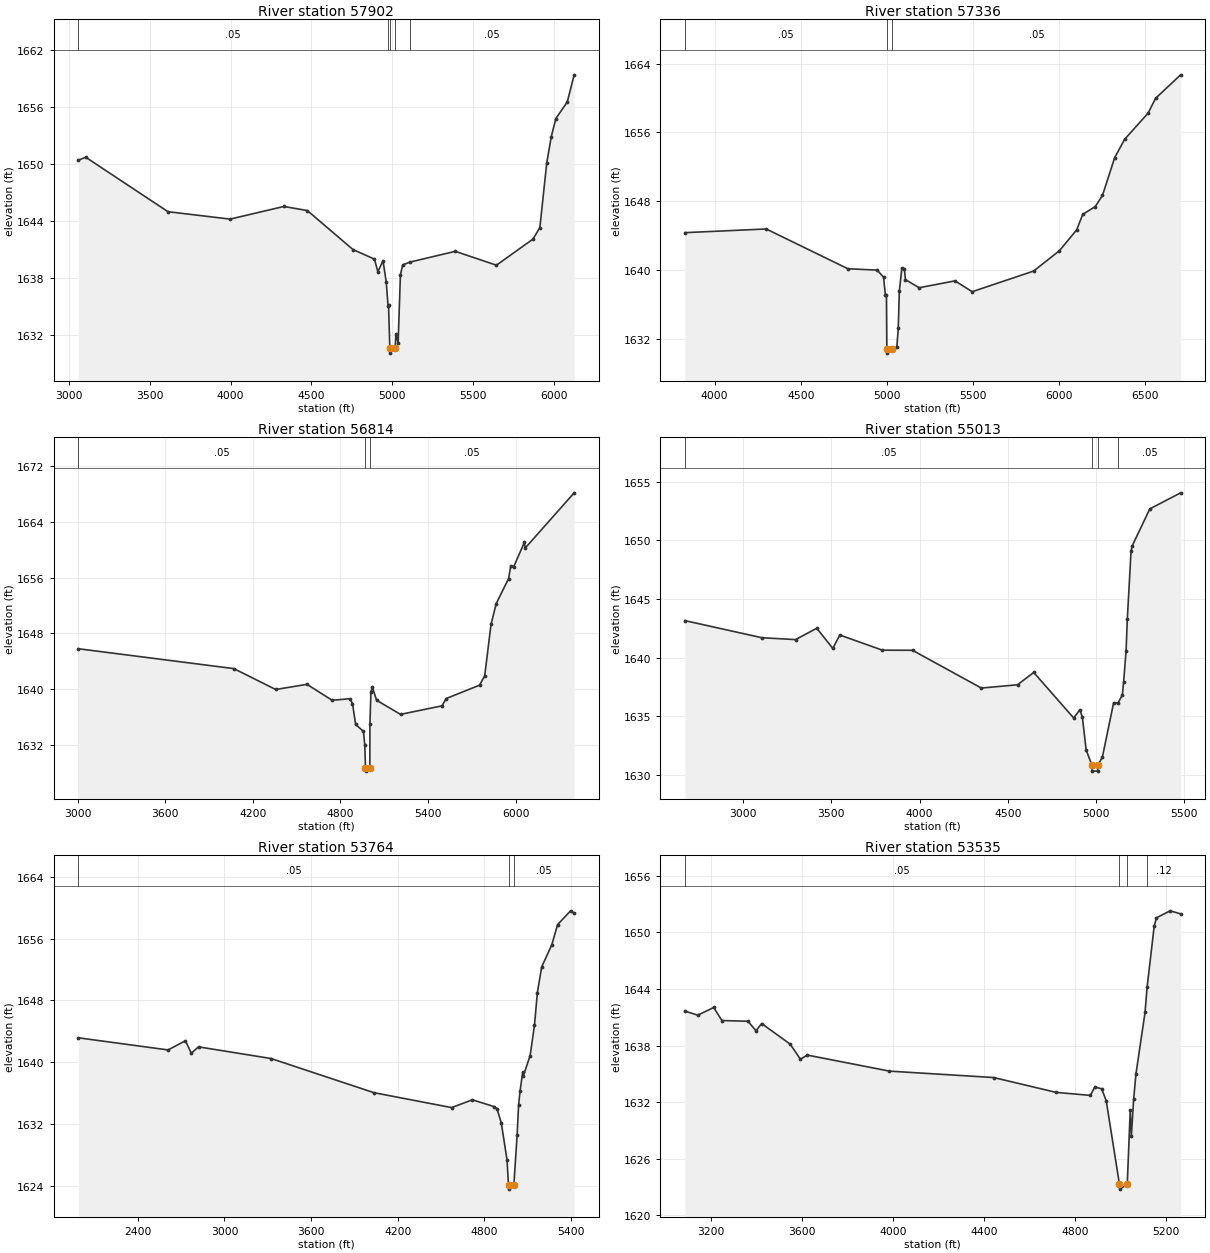
Type RM Length L Ch R = 1,57902,566,566,566
BEGIN DESCRIPTION:
Deadman Creek 64.0
END DESCRIPTION:
XS GIS Cut Line= 3
      1616541.02      6908261.12      1618405.00      6907738.00
      1619205.02      6906937.98
#Sta/Elev= 30
  3058.4 1650.43  3104.1 1650.74  3613.0 1645.01  3997.3 1644.23  4329.7 1645.56
  4475.1 1645.13  4757.3 1641.03  4890.5 1640.02  4911.3 1638.69  4943.3 1639.85
  4963.2 1637.62  4974.4 1635.14  4977.4 1635.19  4985.5 1630.63  4986.0 1630.13
  5018.2 1630.63  5022.7 1632.13  5036.8 1631.20  5051.0 1638.38  5065.1 1639.41
  5110.6 1639.71  5390.4 1640.84  5644.9 1639.38  5871.2 1642.13  5913.6 1643.34
  5956.1 1650.12  5984.3 1652.91  6012.6 1654.81  6083.3 1656.56  6125.8 1659.41
#Mann=5,-1,0
  3058.4    0.05       0  4974.4    0.12       0  4985.5    0.07       0
  5018.2    0.12       0  5110.6    0.05       0
Bank Sta=4985.5,5018.2
Exp/Cntr=0.3,0.1

Type RM Length L Ch R = 1,57336,522,522,522
BEGIN DESCRIPTION:
Deadman Creek 63.0
END DESCRIPTION:
XS GIS Cut Line= 3
      1617751.05      6908731.97      1618755.00      6908138.00
      1620120.40      6907109.04
#Sta/Elev= 30
  3827.6 1644.33  4299.8 1644.76  4773.7 1640.13  4943.4 1639.97  4980.5 1639.16
  4991.2 1637.07  4997.2 1637.07  4999.6 1630.81  5000.1 1630.31  5032.3 1630.81
  5057.6 1631.03  5065.9 1633.20  5072.2 1637.57  5086.7 1640.19  5101.3 1640.08
  5107.6 1638.87  5186.7 1637.92  5394.8 1638.72  5494.8 1637.46  5850.8 1639.86
  6000.7 1642.23  6100.7 1644.65  6136.1 1646.46  6208.7 1647.37  6250.6 1648.67
  6321.4 1653.07  6379.6 1655.21  6515.0 1658.24  6558.7 1659.97  6703.8 1662.70
#Mann=3,-1,0
  3827.6    0.05       0  4999.6    0.05       0  5032.3    0.05       0
Bank Sta=4999.6,5032.3
Exp/Cntr=0.3,0.1

Type RM Length L Ch R = 1,56814,1801,1801,1801
BEGIN DESCRIPTION:
Deadman Creek 62.0
END DESCRIPTION:
XS GIS Cut Line= 3
      1617336.52      6909122.61      1619205.00      6908388.00
      1620304.96      6907538.03
#Sta/Elev= 30
  3003.9 1645.79  4070.1 1642.93  4356.2 1639.93  4571.1 1640.67  4743.0 1638.38
  4863.9 1638.60  4882.7 1637.91  4904.2 1634.90  4957.9 1633.90  4966.9 1631.96
  4971.8 1628.69  4972.4 1628.19  5001.4 1628.69  5002.1 1634.90  5008.9 1639.55
  5018.9 1640.27  5047.8 1638.38  5211.8 1636.35  5496.1 1637.58  5525.1 1638.63
  5753.3 1640.55  5788.6 1641.89  5832.1 1649.30  5867.4 1652.27  5952.6 1655.89
  5967.1 1657.68  5987.9 1657.60  6060.3 1661.08  6066.7 1660.28  6401.7 1668.21
#Mann=3,-1,0
  3003.9    0.05       0  4971.8    0.05       0  5001.4    0.05       0
Bank Sta=4971.8,5001.4
Exp/Cntr=0.3,0.1

Type RM Length L Ch R = 1,55013,1249,1249,1249
BEGIN DESCRIPTION:
Mapping XS 79f90c0c
END DESCRIPTION:
XS GIS Cut Line= 3
      1618150.25      6909096.31      1619732.31      6909244.52
      1620590.30      6908376.20
#Sta/Elev= 30
  2669.6 1643.15  3106.3 1641.69  3297.1 1641.53  3417.6 1642.50  3508.0 1640.78
  3548.2 1641.92  3789.2 1640.63  3960.0 1640.62  4350.0 1637.40  4555.0 1637.68
  4647.0 1638.73  4873.2 1634.85  4908.6 1635.55  4922.7 1634.90  4943.9 1632.13
  4976.8 1630.82  4977.4 1630.32  5009.4 1630.32  5010.0 1630.82  5035.9 1631.51
  5099.5 1636.14  5125.2 1636.14  5149.0 1636.82  5156.0 1637.88  5170.2 1640.57
  5177.3 1643.30  5198.5 1649.09  5205.6 1649.54  5304.6 1652.67  5479.3 1654.04
#Mann=4,-1,0
  2669.6    0.05       0  4976.8    0.07       0  5010.0    0.05       0
  5125.2    0.05       0
Bank Sta=4976.8,5010
Exp/Cntr=0.3,0.1

Type RM Length L Ch R = 1,53764,229,229,229
BEGIN DESCRIPTION:
Mapping XS 1688a6f5
END DESCRIPTION:
XS GIS Cut Line= 3
      1618155.97      6909143.42      1620551.83      6909365.65
      1621579.64      6909407.32
#Sta/Elev= 30
  1987.6 1643.16  2609.3 1641.59  2729.8 1642.78  2770.0 1641.17  2820.2 1641.99
  3322.3 1640.48  4035.3 1636.06  4573.6 1634.13  4717.2 1635.14  4867.3 1634.26
  4887.3 1634.00  4917.3 1632.18  4957.4 1627.36  4967.4 1624.13  4970.3 1624.08
  4971.0 1623.58  5004.5 1624.08  5027.4 1630.62  5037.4 1634.42  5047.4 1636.24
  5065.7 1638.69  5070.7 1638.24  5117.5 1640.87  5147.5 1644.78  5167.5 1649.00
  5197.6 1652.34  5267.6 1655.20  5307.7 1657.81  5397.7 1659.59  5422.4 1659.28
#Mann=3,-1,0
  1987.6    0.05       0  4970.3    0.05       0  5004.5    0.05       0
Bank Sta=4970.3,5004.5
Exp/Cntr=0.3,0.1

Type RM Length L Ch R = 1,53535,605,605,605
BEGIN DESCRIPTION:
Mapping XS c0c2f554
END DESCRIPTION:
XS GIS Cut Line= 2
      1619378.21      6909442.04      1621550.93      6909587.81
#Sta/Elev= 30
  3086.2 1641.65  3143.1 1641.22  3213.3 1642.03  3249.2 1640.65  3363.6 1640.57
  3399.0 1639.57  3423.7 1640.33  3548.9 1638.15  3594.1 1636.55  3624.2 1636.99
  3985.0 1635.29  4443.0 1634.61  4716.6 1633.04  4867.0 1632.72  4887.0 1633.60
  4917.1 1633.42  4937.1 1632.15  4995.2 1623.29  4995.9 1622.79  5029.4 1623.29
  5042.5 1631.18  5047.5 1628.44  5057.4 1632.29  5067.4 1634.96  5107.5 1641.51
  5116.6 1644.19  5147.6 1650.61  5157.6 1651.53  5217.8 1652.27  5263.8 1651.95
#Mann=4,-1,0
  3086.2    0.05       0  4995.2    0.03       0  5029.4    0.05       0
  5116.6    0.12       0
Bank Sta=4995.2,5029.4
Exp/Cntr=0.3,0.1

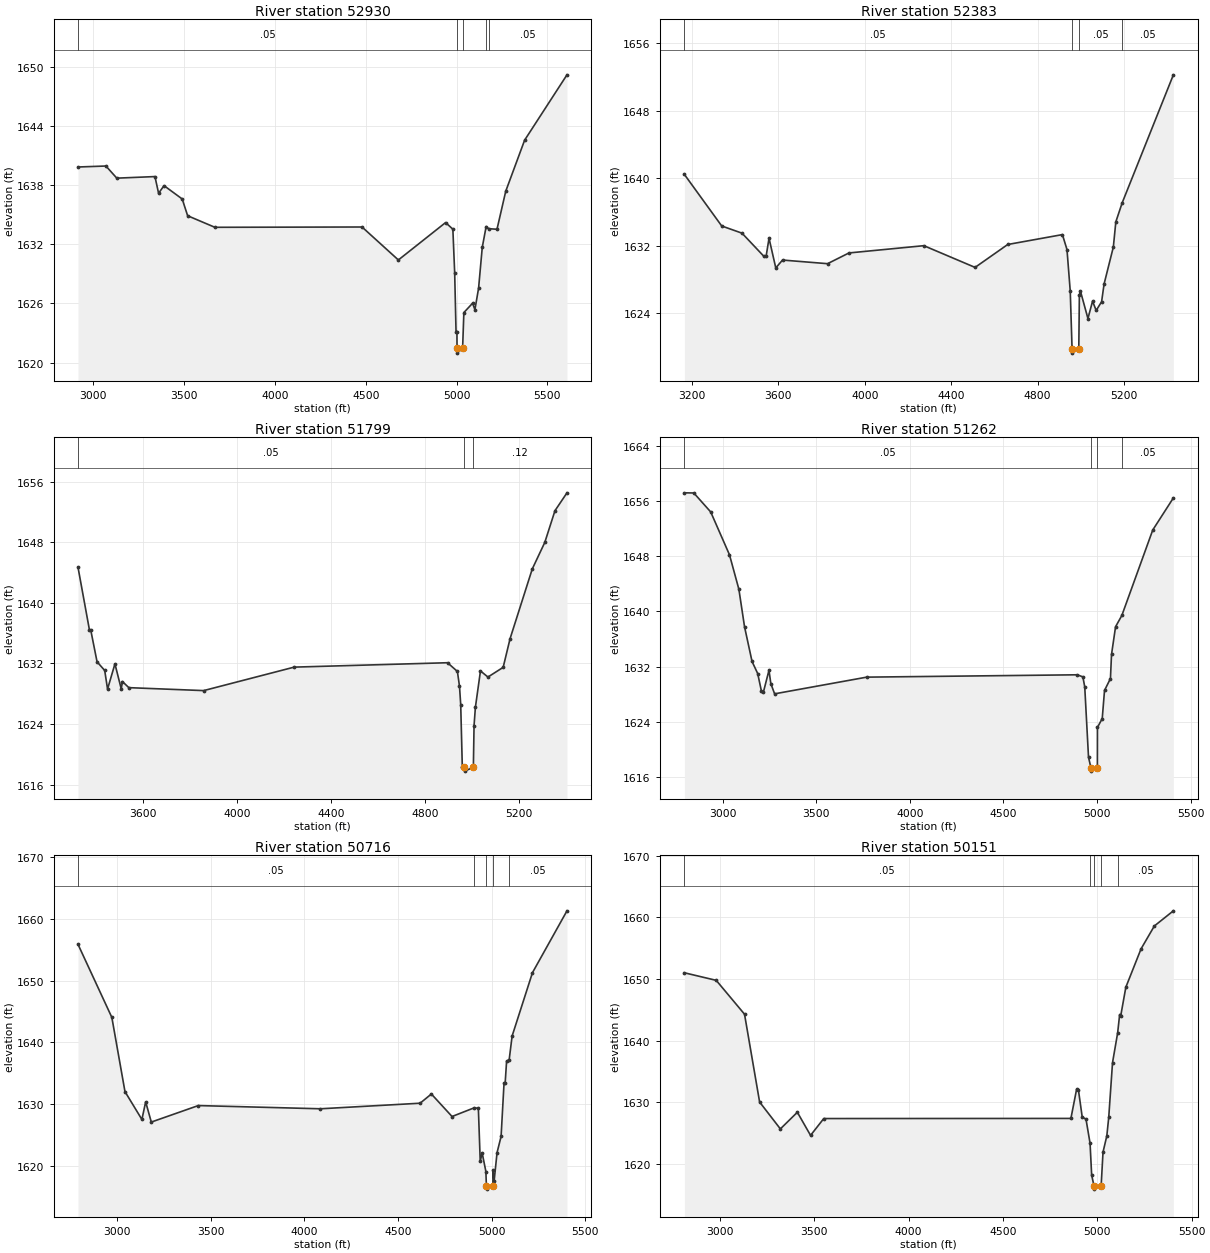
Type RM Length L Ch R = 1,52930,547,547,547
BEGIN DESCRIPTION:
Deadman Creek 56.0
END DESCRIPTION:
XS GIS Cut Line= 3
      1619371.30      6910067.04      1621455.00      6910088.00
      1622055.02      6909988.00
#Sta/Elev= 30
  2915.6 1639.83  3069.3 1639.93  3129.3 1638.70  3339.3 1638.86  3359.3 1637.17
  3389.3 1637.94  3489.3 1636.59  3519.3 1634.89  3669.3 1633.72  4479.4 1633.75
  4679.4 1630.41  4939.4 1634.20  4979.4 1633.53  4989.4 1629.12  4996.9 1623.15
  5001.9 1623.15  5002.3 1621.47  5003.0 1620.97  5033.1 1621.47  5040.0 1625.08
  5088.1 1626.03  5100.8 1625.37  5121.1 1627.56  5141.3 1631.69  5162.7 1633.80
  5176.1 1633.58  5222.4 1633.52  5270.6 1637.38  5374.5 1642.55  5607.7 1649.17
#Mann=5,-1,0
  2915.6    0.05       0  5002.3    0.03       0  5033.1    0.05       0
  5162.7    0.12       0  5176.1    0.05       0
Bank Sta=5002.3,5033.1
Exp/Cntr=0.3,0.1

Type RM Length L Ch R = 1,52383,584,584,584
BEGIN DESCRIPTION:
Deadman Creek 55.0
END DESCRIPTION:
XS GIS Cut Line= 4
      1619987.55      6911169.43      1621571.99      6910625.15
      1621705.00      6910538.00      1622104.97      6910388.01
#Sta/Elev= 30
  3166.1 1640.44  3338.8 1634.34  3432.6 1633.49  3533.5 1630.76  3544.1 1630.75
  3557.6 1632.89  3588.8 1629.38  3620.1 1630.31  3828.3 1629.88  3927.3 1631.15
  4273.6 1632.01  4510.5 1629.44  4661.5 1632.15  4914.5 1633.32  4935.6 1631.55
  4950.7 1626.62  4959.1 1619.80  4959.7 1619.30  4990.2 1619.80  4992.9 1626.14
  4997.4 1626.68  5032.5 1623.39  5053.8 1625.44  5070.7 1624.35  5095.7 1625.38
  5107.2 1627.48  5150.0 1631.85  5161.5 1634.83  5190.9 1637.08  5427.6 1652.22
#Mann=4,-1,0
  3166.1    0.05       0  4959.1    0.07       0  4990.2    0.05       0
  5190.9    0.05       0
Bank Sta=4959.1,4990.2
Exp/Cntr=0.3,0.1

Type RM Length L Ch R = 1,51799,537,537,537
BEGIN DESCRIPTION:
Deadman Creek 54.0
END DESCRIPTION:
XS GIS Cut Line= 3
      1620455.05      6911487.99      1622055.00      6910988.00
      1622405.03      6910787.98
#Sta/Elev= 30
  3323.3 1644.71  3372.0 1636.43  3377.2 1636.47  3404.4 1632.22  3436.9 1631.08
  3449.0 1628.62  3480.4 1631.95  3507.1 1628.66  3512.4 1629.61  3539.6 1628.81
  3857.6 1628.42  4242.6 1631.52  4894.8 1632.10  4936.7 1630.95  4945.6 1629.00
  4950.8 1626.57  4957.6 1618.32  4966.6 1618.29  4967.3 1617.79  5004.6 1618.29
  5007.5 1623.79  5013.2 1626.21  5034.8 1631.02  5066.5 1630.21  5131.3 1631.49
  5160.8 1635.29  5255.1 1644.48  5308.4 1647.99  5351.6 1652.17  5402.7 1654.53
#Mann=3,-1,0
  3323.3    0.05       0  4966.6    0.07       0  5004.6    0.12       0
Bank Sta=4966.6,5004.6
Exp/Cntr=0.3,0.1

Type RM Length L Ch R = 1,51262,546,546,546
BEGIN DESCRIPTION:
Deadman Creek 53.0
END DESCRIPTION:
XS GIS Cut Line= 3
      1620204.96      6911588.00      1622405.00      6911388.00
      1622604.99      6911038.03
#Sta/Elev= 30
  2796.0 1657.19  2846.3 1657.17  2936.6 1654.42  3037.0 1648.20  3087.2 1643.20
  3117.4 1637.76  3157.5 1632.73  3187.7 1630.98  3207.7 1628.42  3217.8 1628.25
  3247.9 1631.45  3257.9 1629.52  3278.0 1628.04  3770.0 1630.46  4894.7 1630.80
  4924.8 1630.50  4934.8 1629.04  4954.9 1618.85  4967.7 1617.33  4968.4 1616.83
  5002.3 1617.33  5002.6 1623.17  5028.2 1624.45  5040.4 1628.53  5072.1 1630.26
  5077.8 1633.75  5099.4 1637.77  5132.9 1639.40  5298.1 1651.80  5408.2 1656.45
#Mann=4,-1,0
  2796.0    0.05       0  4967.7    0.07       0  5002.3    0.05       0
  5132.9    0.05       0
Bank Sta=4967.7,5002.3
Exp/Cntr=0.3,0.1

Type RM Length L Ch R = 1,50716,565,565,565
BEGIN DESCRIPTION:
Deadman Creek 52.0
END DESCRIPTION:
XS GIS Cut Line= 3
      1620354.98      6911688.00      1622555.00      6911888.00
      1622905.00      6912088.00
#Sta/Elev= 30
  2791.0 1655.87  2971.8 1644.05  3042.0 1632.04  3132.4 1627.53  3152.5 1630.38
  3182.6 1627.11  3433.7 1629.78  4086.3 1629.26  4618.5 1630.16  4678.8 1631.65
  4789.2 1628.01  4908.8 1629.43  4929.8 1629.32  4939.8 1620.74  4949.9 1622.13
  4970.0 1619.11  4972.7 1616.76  4973.4 1616.26  5007.4 1616.76  5008.0 1619.29
  5013.8 1617.50  5029.6 1622.16  5051.2 1624.78  5067.0 1633.44  5072.8 1633.36
  5080.7 1636.99  5094.2 1637.15  5110.2 1641.04  5218.9 1651.29  5403.2 1661.29
#Mann=5,-1,0
  2791.0    0.05       0  4908.8    0.12       0  4972.7    0.07       0
  5007.4    0.12       0  5094.2    0.05       0
Bank Sta=4972.7,5007.4
Exp/Cntr=0.3,0.1

Type RM Length L Ch R = 1,50151,734,734,734
BEGIN DESCRIPTION:
Deadman Creek 51.0
END DESCRIPTION:
XS GIS Cut Line= 3
      1620316.24      6912424.31      1622505.00      6912438.00
      1622904.99      6912388.00
#Sta/Elev= 30
  2811.2 1651.02  2980.0 1649.79  3130.0 1644.30  3210.0 1630.05  3320.0 1625.69
  3410.0 1628.39  3480.0 1624.64  3550.0 1627.37  4860.0 1627.39  4890.0 1632.09
  4900.0 1631.98  4920.0 1627.61  4940.0 1627.27  4961.5 1623.37  4970.0 1618.19
  4982.6 1616.42  4983.3 1615.92  5017.4 1616.42  5020.2 1616.42  5030.2 1621.92
  5050.4 1624.57  5060.5 1627.56  5080.6 1636.44  5107.8 1641.27  5118.4 1644.25
  5123.5 1643.94  5151.2 1648.68  5231.8 1654.90  5302.3 1658.61  5403.1 1661.07
#Mann=5,-1,0
  2811.2    0.05       0  4961.5    0.12       0  4982.6    0.07       0
  5017.4    0.12       0  5107.8    0.05       0
Bank Sta=4982.6,5017.4
Exp/Cntr=0.3,0.1

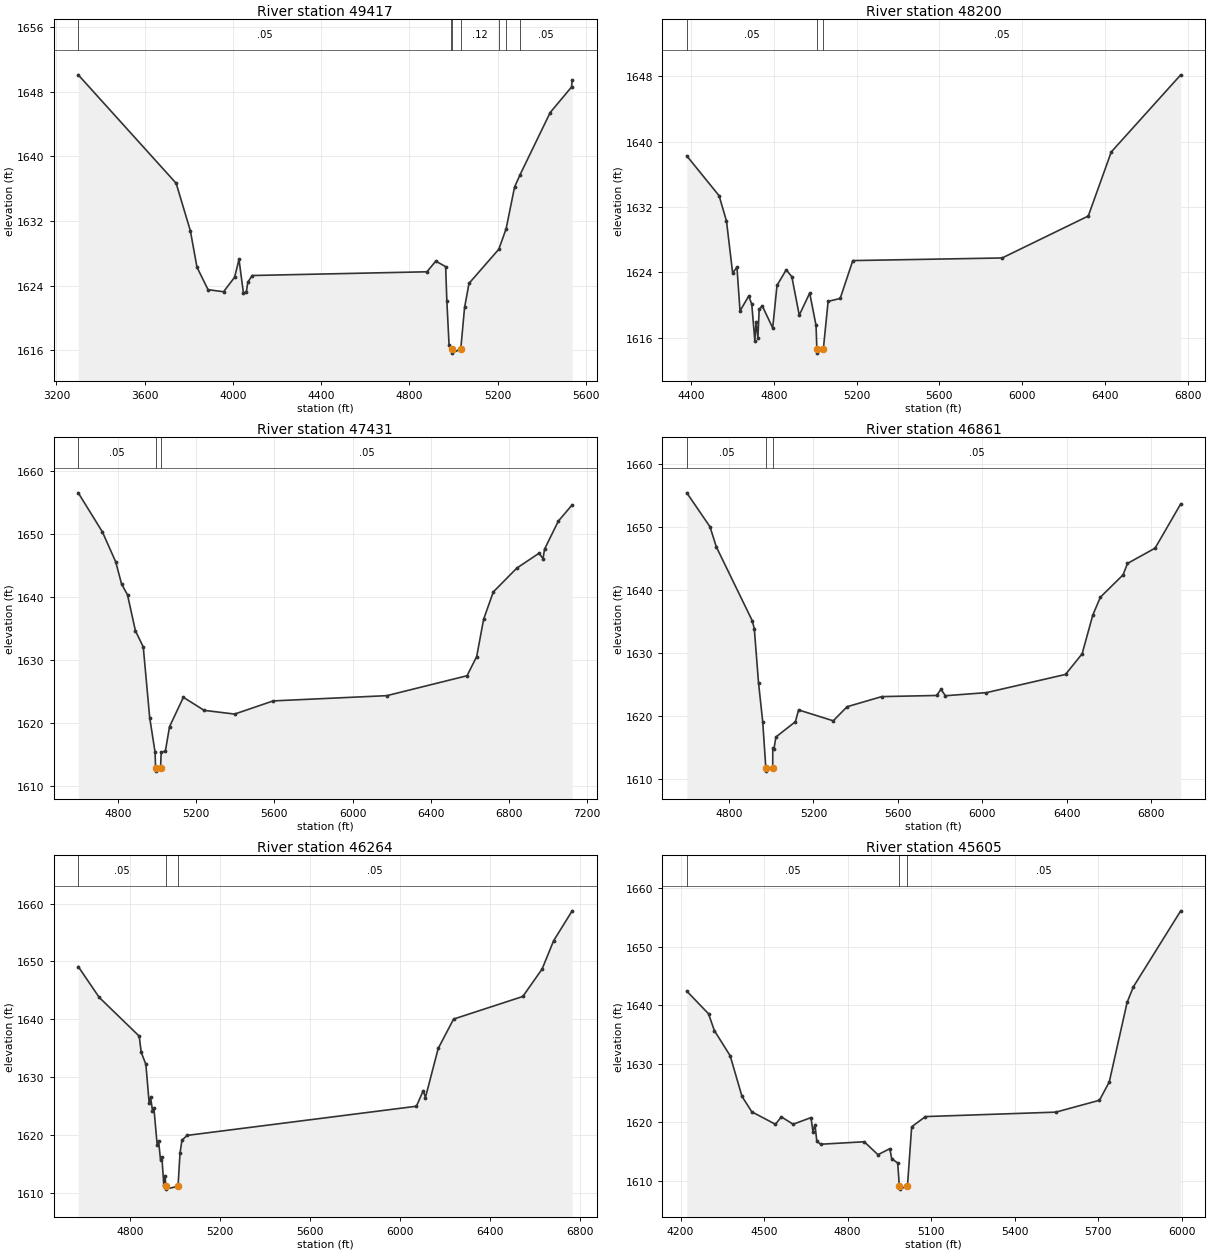
Type RM Length L Ch R = 1,49417,1217,1217,1217
BEGIN DESCRIPTION:
Mapping XS 75bef355
END DESCRIPTION:
XS GIS Cut Line= 4
      1620607.86      6913221.18      1622165.19      6913122.22
      1622399.56      6913101.39      1622784.69      6912882.80
#Sta/Elev= 30
  3299.1 1650.07  3742.8 1636.66  3807.3 1630.78  3837.3 1626.28  3887.4 1623.50
  3957.6 1623.24  4007.7 1625.03  4027.7 1627.24  4047.7 1623.11  4060.8 1623.20
  4067.8 1624.43  4087.8 1625.25  4879.5 1625.71  4919.6 1627.03  4964.3 1626.35
  4969.8 1622.06  4979.9 1616.61  4990.7 1616.15  4991.0 1616.15  4991.8 1615.65
  5032.8 1616.15  5050.1 1621.30  5070.2 1624.28  5205.3 1628.50  5238.5 1631.04
  5276.6 1636.19  5301.7 1637.72  5438.2 1645.41  5534.8 1648.56  5537.7 1649.39
#Mann=7,-1,0
  3299.1    0.05       0  4990.7    0.12       0  4991.0    0.07       0
  5032.8    0.12       0  5205.3    0.05       0  5238.5    0.12       0
  5301.7    0.05       0
Bank Sta=4991,5032.8
Exp/Cntr=0.3,0.1

Type RM Length L Ch R = 1,48200,769,769,769
BEGIN DESCRIPTION:
Deadman Creek 50.0
END DESCRIPTION:
XS GIS Cut Line= 3
      1621201.62      6914242.03      1621706.85      6913887.85
      1623279.77      6913080.56
#Sta/Elev= 30
  4380.1 1638.27  4536.0 1633.39  4571.8 1630.28  4601.4 1623.93  4622.3 1624.62
  4637.1 1619.27  4679.0 1621.09  4693.8 1620.10  4708.6 1615.63  4714.7 1617.92
  4723.4 1615.99  4729.6 1619.45  4744.4 1619.90  4794.9 1617.19  4815.8 1622.41
  4860.3 1624.31  4887.3 1623.46  4923.1 1618.75  4973.6 1621.46  5004.2 1617.49
  5008.1 1614.60  5008.7 1614.10  5039.4 1614.60  5062.5 1620.44  5120.8 1620.80
  5181.7 1625.44  5902.7 1625.76  6318.7 1630.90  6429.7 1638.75  6765.1 1648.20
#Mann=3,-1,0
  4380.1    0.05       0  5008.1    0.05       0  5039.4    0.05       0
Bank Sta=5008.1,5039.4
Exp/Cntr=0.3,0.1

Type RM Length L Ch R = 1,47431,570,570,570
BEGIN DESCRIPTION:
Deadman Creek 49.0
END DESCRIPTION:
XS GIS Cut Line= 3
      1621805.00      6914937.96      1621855.00      6914538.00
      1623405.02      6913087.98
#Sta/Elev= 30
  4596.8 1656.47  4720.2 1650.28  4788.2 1645.54  4818.5 1642.00  4848.7 1640.30
  4889.0 1634.61  4929.3 1632.02  4962.1 1620.83  4989.8 1615.31  4992.2 1612.83
  4992.8 1612.33  5017.6 1612.83  5021.1 1615.36  5042.1 1615.46  5063.6 1619.38
  5134.4 1624.04  5240.5 1621.97  5396.3 1621.38  5594.1 1623.47  6174.5 1624.30
  6584.8 1627.46  6634.1 1630.49  6669.8 1636.43  6719.1 1640.75  6839.3 1644.53
  6952.6 1646.88  6973.6 1646.05  6981.0 1647.53  7051.8 1651.99  7122.4 1654.56
#Mann=3,-1,0
  4596.8    0.05       0  4992.2    0.05       0  5017.6    0.05       0
Bank Sta=4992.2,5017.6
Exp/Cntr=0.3,0.1

Type RM Length L Ch R = 1,46861,597,597,597
BEGIN DESCRIPTION:
Deadman Creek 48.0
END DESCRIPTION:
XS GIS Cut Line= 3
      1622355.00      6915138.03      1622355.00      6914738.00
      1623455.01      6913137.99
#Sta/Elev= 30
  4599.7 1655.48  4709.7 1650.08  4739.7 1646.88  4909.7 1635.15  4919.7 1633.88
  4939.7 1625.28  4959.7 1619.03  4974.4 1611.69  4975.3 1611.19  5007.1 1611.69
  5007.2 1614.88  5013.2 1614.76  5022.1 1616.62  5114.7 1619.06  5129.6 1620.93
  5294.0 1619.20  5359.7 1621.44  5524.0 1623.05  5783.8 1623.23  5804.8 1624.20
  5825.8 1623.19  6019.9 1623.68  6395.3 1626.58  6473.9 1629.86  6524.6 1636.03
  6560.5 1638.87  6668.1 1642.43  6689.0 1644.24  6820.0 1646.68  6941.4 1653.72
#Mann=3,-1,0
  4599.7    0.05       0  4974.4    0.05       0  5007.1    0.05       0
Bank Sta=4974.4,5007.1
Exp/Cntr=0.3,0.1

Type RM Length L Ch R = 1,46264,659,659,659
BEGIN DESCRIPTION:
Deadman Creek 47.0
END DESCRIPTION:
XS GIS Cut Line= 3
      1622654.98      6915038.02      1622904.77      6914689.93
      1623654.98      6913088.04
#Sta/Elev= 30
  4570.0 1649.12  4663.4 1643.78  4841.4 1637.07  4850.0 1634.30  4870.9 1632.19
  4885.6 1625.47  4891.8 1626.51  4900.3 1624.19  4906.5 1624.65  4921.2 1618.25
  4927.4 1618.97  4936.0 1615.64  4942.1 1616.11  4950.7 1611.30  4956.8 1612.83
  4959.0 1611.09  4960.0 1610.59  5014.0 1611.09  5022.7 1616.78  5031.3 1619.05
  5054.1 1619.89  6074.5 1624.94  6104.8 1627.64  6114.6 1626.45  6171.3 1634.94
  6239.8 1640.03  6547.7 1643.94  6633.5 1648.69  6684.7 1653.58  6767.3 1658.77
#Mann=3,-1,0
  4570.0    0.05       0  4959.0    0.05       0  5014.0    0.05       0
Bank Sta=4959,5014
Exp/Cntr=0.3,0.1

Type RM Length L Ch R = 1,45605,517,517,517
BEGIN DESCRIPTION:
Deadman Creek 46.0
END DESCRIPTION:
XS GIS Cut Line= 3
      1622905.01      6915037.99      1623472.48      6914518.06
      1624104.99      6913738.02
#Sta/Elev= 30
  4222.3 1642.38  4300.3 1638.52  4321.3 1635.65  4378.0 1631.35  4420.5 1624.41
  4455.7 1621.78  4540.8 1619.64  4561.7 1620.92  4604.3 1619.65  4668.4 1620.79
  4675.2 1618.40  4682.6 1619.56  4689.4 1616.72  4703.6 1616.24  4859.6 1616.66
  4908.9 1614.45  4951.5 1615.48  4958.2 1613.77  4979.8 1613.02  4985.6 1609.07
  4986.3 1608.57  5014.8 1609.07  5029.9 1619.22  5079.5 1620.96  5547.9 1621.72
  5704.5 1623.75  5739.7 1626.90  5803.7 1640.47  5826.0 1643.11  5996.2 1656.10
#Mann=3,-1,0
  4222.3    0.05       0  4985.6    0.03       0  5014.8    0.05       0
Bank Sta=4985.6,5014.8
Exp/Cntr=0.3,0.1

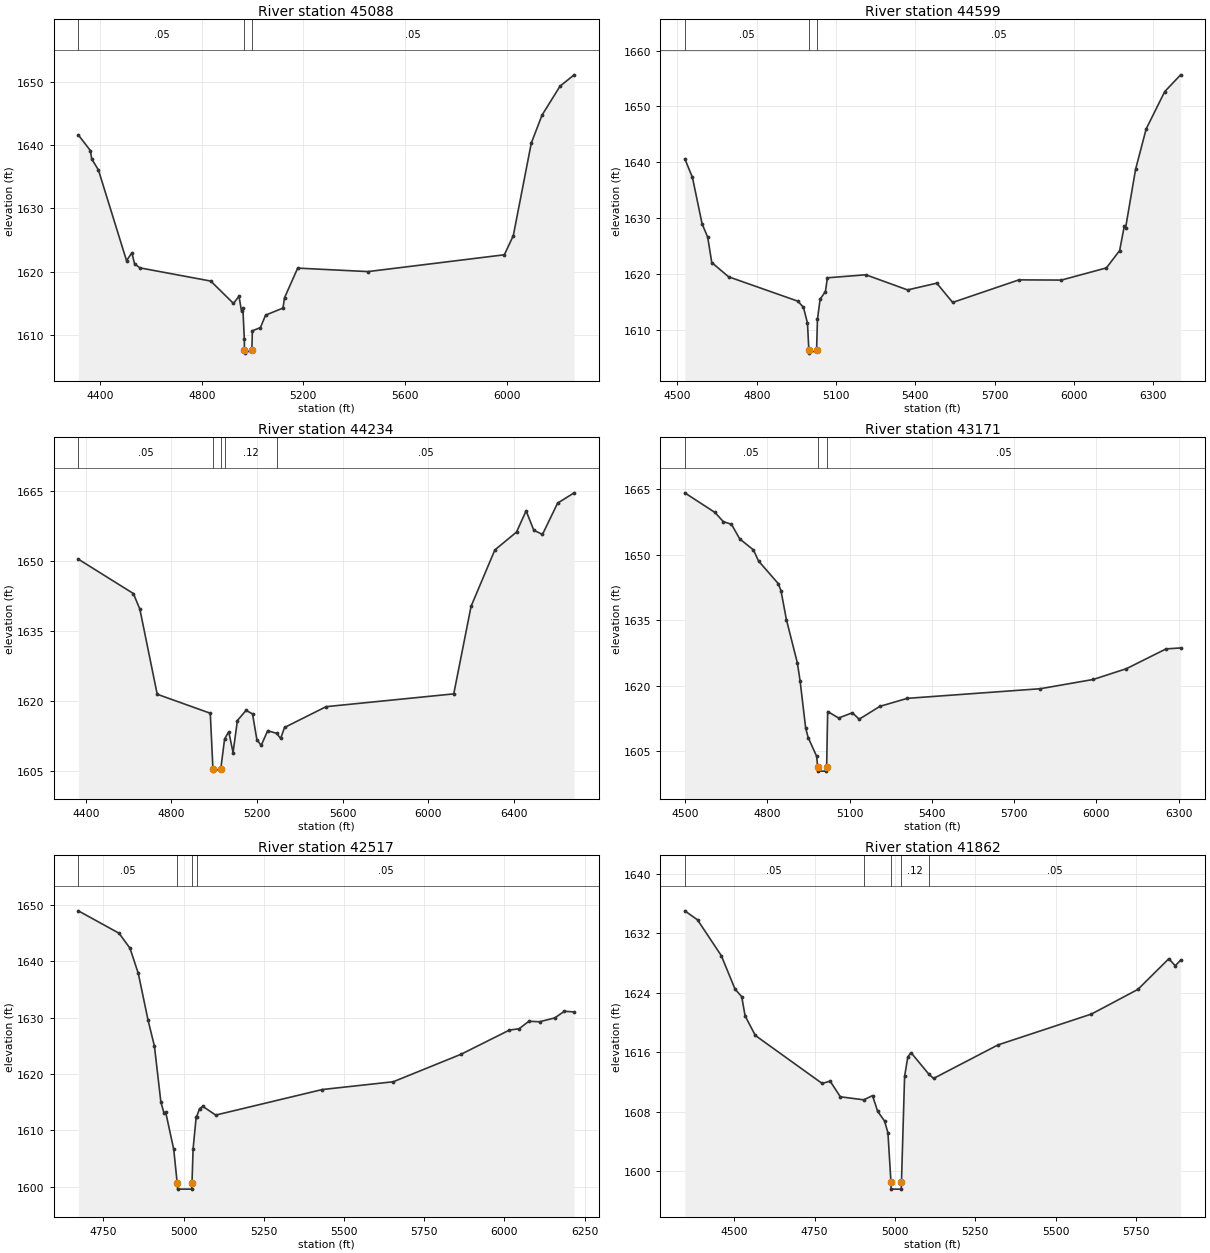
Type RM Length L Ch R = 1,45088,489,489,489
BEGIN DESCRIPTION:
Deadman Creek 45.0
END DESCRIPTION:
XS GIS Cut Line= 3
      1623005.00      6915138.00      1623909.98      6914835.77
      1624628.71      6914143.08
#Sta/Elev= 30
  4314.1 1641.63  4361.5 1639.16  4366.8 1637.83  4393.1 1636.10  4503.9 1621.74
  4525.0 1622.98  4535.5 1621.24  4556.6 1620.60  4835.5 1618.51  4925.0 1614.97
  4946.7 1616.12  4956.6 1613.78  4961.9 1614.24  4967.8 1609.27  4968.1 1607.61
  4968.8 1607.11  4997.3 1607.61  4999.4 1610.64  5031.0 1611.15  5051.4 1613.12
  5119.9 1614.24  5125.9 1615.86  5177.8 1620.56  5454.2 1620.01  5991.6 1622.67
  6026.8 1625.70  6097.6 1640.34  6140.0 1644.77  6210.8 1649.35  6266.4 1651.14
#Mann=3,-1,0
  4314.1    0.05       0  4968.1    0.03       0  4997.3    0.05       0
Bank Sta=4968.1,4997.3
Exp/Cntr=0.3,0.1

Type RM Length L Ch R = 1,44599,365,365,365
BEGIN DESCRIPTION:
Deadman Creek 44.0
END DESCRIPTION:
XS GIS Cut Line= 3
      1623405.03      6915587.98      1623805.00      6915338.00
      1625204.97      6915238.00
#Sta/Elev= 30
  4527.9 1640.63  4556.8 1637.29  4593.3 1628.99  4614.5 1626.60  4629.9 1622.06
  4693.5 1619.51  4955.3 1615.15  4976.6 1614.05  4991.9 1611.22  4997.1 1606.35
  4997.8 1605.85  5026.3 1606.35  5029.6 1611.88  5039.7 1615.51  5059.7 1616.86
  5067.2 1619.33  5212.6 1619.87  5370.5 1617.16  5480.8 1618.37  5540.9 1614.92
  5791.6 1618.96  5952.0 1618.92  6122.4 1621.10  6172.5 1624.21  6190.1 1628.61
  6195.1 1628.30  6232.7 1638.73  6272.8 1645.97  6343.0 1652.65  6403.1 1655.65
#Mann=3,-1,0
  4527.9    0.05       0  4997.1    0.05       0  5026.3    0.05       0
Bank Sta=4997.1,5026.3
Exp/Cntr=0.3,0.1

Type RM Length L Ch R = 1,44234,1063,1063,1063
BEGIN DESCRIPTION:
Deadman Creek 43.0
END DESCRIPTION:
XS GIS Cut Line= 3
      1623191.23      6915799.31      1623816.23      6915700.35
      1625481.43      6915460.98
#Sta/Elev= 30
  4365.5 1650.33  4622.4 1642.97  4652.8 1639.62  4733.8 1621.39  4981.6 1617.32
  4994.0 1605.42  4994.9 1604.92  5030.6 1605.42  5048.5 1611.82  5067.8 1613.35
  5088.0 1608.89  5108.2 1615.76  5148.6 1617.94  5178.9 1617.18  5199.1 1611.66
  5219.3 1610.43  5249.6 1613.58  5291.1 1613.02  5310.2 1611.92  5328.2 1614.27
  5522.4 1618.73  6118.4 1621.47  6199.3 1640.23  6310.2 1652.30  6411.4 1656.13
  6456.2 1660.68  6492.3 1656.52  6532.7 1655.63  6603.4 1662.34  6680.6 1664.54
#Mann=5,-1,0
  4365.5    0.05       0  4994.0    0.05       0  5030.6    0.05       0
  5048.5    0.12       0  5291.1    0.05       0
Bank Sta=4994,5030.6
Exp/Cntr=0.3,0.1

Type RM Length L Ch R = 1,43171,654,654,654
BEGIN DESCRIPTION:
Deadman Creek 42.0
END DESCRIPTION:
XS GIS Cut Line= 3
      1623205.04      6916538.00      1624165.19      6916590.97
      1624847.48      6917090.98
#Sta/Elev= 30
  4499.4 1664.20  4609.5 1659.69  4639.6 1657.61  4669.6 1656.98  4699.7 1653.63
  4749.7 1651.11  4768.2 1648.57  4839.9 1643.40  4849.9 1641.79  4869.9 1635.10
  4910.0 1625.13  4920.0 1620.94  4940.0 1610.27  4949.1 1608.09  4980.1 1603.77
  4983.7 1601.38  4984.4 1600.38  5015.7 1600.38  5016.5 1601.38  5020.2 1614.05
  5060.2 1612.56  5110.3 1613.77  5135.0 1612.28  5210.4 1615.23  5310.6 1617.07
  5795.5 1619.28  5988.3 1621.40  6109.5 1623.88  6253.8 1628.41  6306.9 1628.63
#Mann=3,-1,0
  4499.4    0.05       0  4983.7    0.05       0  5016.5    0.05       0
Bank Sta=4983.7,5016.5
Exp/Cntr=0.3,0.1

Type RM Length L Ch R = 1,42517,655,655,655
BEGIN DESCRIPTION:
Deadman Creek 41.0
END DESCRIPTION:
XS GIS Cut Line= 3
      1623378.76      6917158.68      1623705.00      6917188.00
      1624915.17      6917325.35
#Sta/Elev= 30
  4672.0 1648.94  4798.8 1644.97  4832.9 1642.32  4859.0 1637.83  4889.1 1629.61
  4909.2 1624.94  4929.3 1615.03  4939.0 1613.08  4944.0 1613.31  4969.4 1606.63
  4980.3 1600.59  4981.4 1599.59  5025.2 1599.59  5026.3 1600.59  5029.7 1606.72
  5039.3 1612.37  5040.6 1612.42  5049.9 1613.86  5059.9 1614.27  5100.2 1612.72
  5432.3 1617.25  5653.7 1618.63  5865.1 1623.51  6015.2 1627.78  6046.2 1628.04
  6076.4 1629.36  6109.8 1629.27  6156.9 1629.95  6187.1 1631.13  6217.5 1631.01
#Mann=4,-1,0
  4672.0    0.05       0  4980.3    0.07       0  5026.3    0.05       0
  5040.6    0.05       0
Bank Sta=4980.3,5026.3
Exp/Cntr=0.3,0.1

Type RM Length L Ch R = 1,41862,679,679,679
BEGIN DESCRIPTION:
Deadman Creek 40.0
END DESCRIPTION:
XS GIS Cut Line= 3
      1623237.62      6917573.99      1623866.07      6917789.26
      1624741.65      6917840.88
#Sta/Elev= 30
  4346.7 1635.04  4386.2 1633.83  4460.2 1629.01  4502.9 1624.51  4523.6 1623.50
  4534.2 1620.91  4565.9 1618.28  4773.8 1611.82  4798.5 1612.14  4830.2 1610.03
  4902.9 1609.62  4930.3 1610.19  4946.4 1608.06  4967.6 1606.78  4978.2 1605.19
  4987.5 1598.61  4988.3 1597.61  5019.6 1597.61  5020.3 1598.61  5030.0 1612.77
  5040.0 1615.38  5050.0 1615.97  5106.2 1613.03  5120.1 1612.50  5320.5 1617.01
  5611.0 1621.16  5755.2 1624.47  5851.4 1628.60  5871.4 1627.65  5888.1 1628.41
#Mann=5,-1,0
  4346.7    0.05       0  4902.9    0.12       0  4987.5    0.07       0
  5020.3    0.12       0  5106.2    0.05       0
Bank Sta=4987.5,5020.3
Exp/Cntr=0.3,0.1