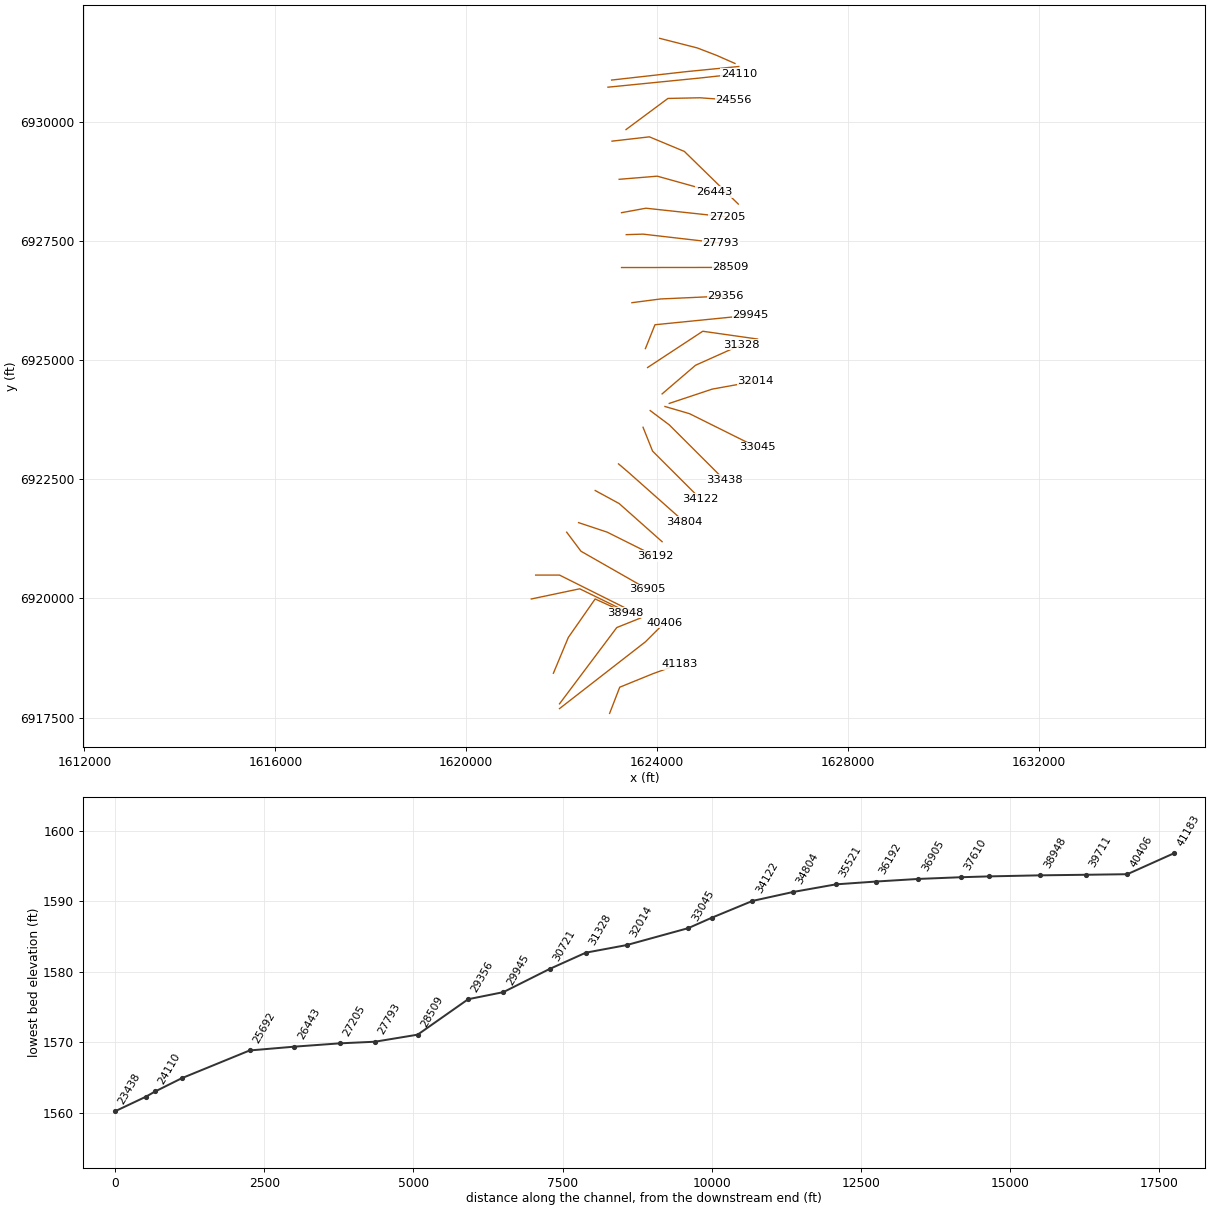
HEC-RAS study Deadman Creek.prj: Deadman Creek Base Level Engineering

--- Deadman Creek.g01 (geometry) --- (continued)

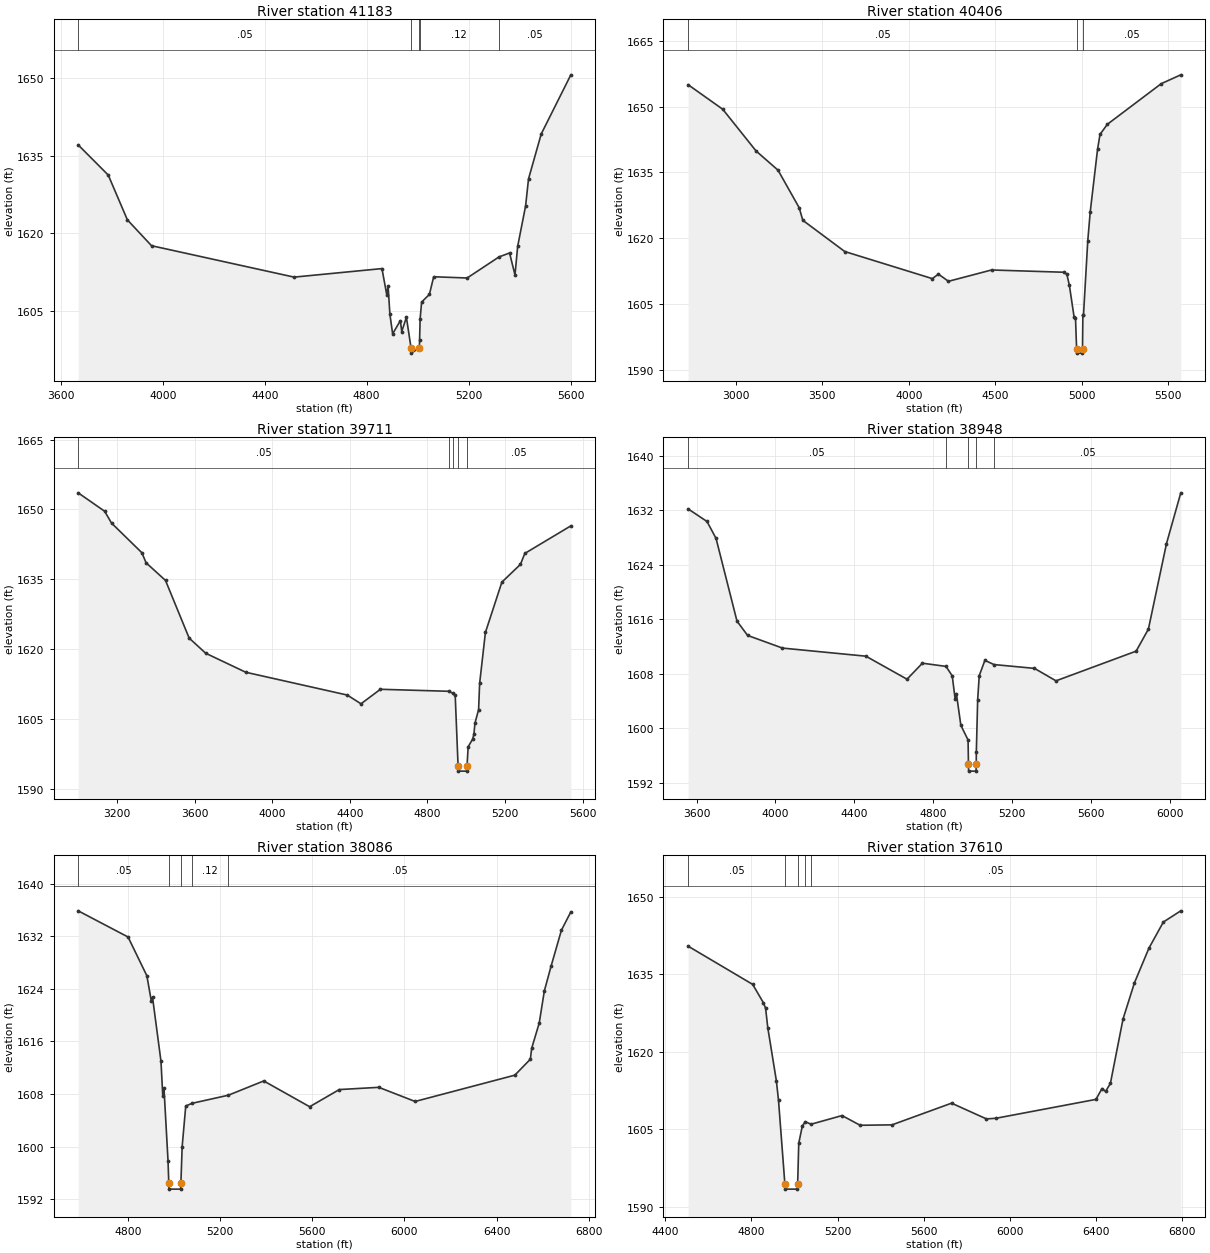
Type RM Length L Ch R = 1,41183,777,777,777
BEGIN DESCRIPTION:
Deadman Creek 39.0
END DESCRIPTION:
XS GIS Cut Line= 4
      1623004.98      6917587.96      1623216.76      6918136.48
      1623909.98      6918419.10      1624471.20      6918621.76
#Sta/Elev= 30
  3668.0 1637.09  3786.0 1631.25  3861.0 1622.59  3955.8 1617.58  4515.2 1611.50
  4860.1 1613.15  4878.8 1608.12  4884.2 1609.73  4891.2 1604.33  4902.0 1600.52
  4932.3 1603.08  4937.7 1600.97  4956.0 1603.73  4974.2 1597.79  4974.9 1596.79
  5007.0 1597.79  5007.8 1599.35  5009.9 1603.45  5015.7 1606.67  5046.3 1608.16
  5063.1 1611.57  5194.4 1611.33  5319.1 1615.40  5360.8 1616.17  5382.1 1611.93
  5392.7 1617.47  5423.8 1625.28  5435.2 1630.50  5485.1 1639.21  5601.3 1650.65
#Mann=5,-1,0
  3668.0    0.05       0  4974.2    0.03       0  5007.0    0.05       0
  5007.8    0.12       0  5319.1    0.05       0
Bank Sta=4974.2,5007
Exp/Cntr=0.3,0.1

Type RM Length L Ch R = 1,40406,695,695,695
BEGIN DESCRIPTION:
Deadman Creek 38.0
END DESCRIPTION:
XS GIS Cut Line= 3
      1621954.99      6917688.00      1623755.00      6919088.00
      1624154.97      6919487.97
#Sta/Elev= 30
  2725.5 1654.98  2925.5 1649.39  3118.2 1639.88  3244.9 1635.51  3367.1 1626.96
  3387.9 1624.10  3630.4 1616.98  4136.2 1610.81  4171.5 1611.83  4229.5 1610.20
  4478.3 1612.78  4899.1 1612.26  4913.6 1611.76  4928.0 1609.27  4955.2 1602.06
  4963.3 1601.85  4969.7 1594.84  4970.9 1594.84  4971.7 1593.84  5003.0 1593.84
  5003.8 1594.84  5005.9 1602.45  5009.4 1602.45  5034.1 1619.37  5048.3 1625.98
  5090.7 1640.25  5104.9 1643.66  5147.3 1645.96  5458.4 1655.21  5571.5 1657.23
#Mann=3,-1,0
  2725.5    0.05       0  4970.9    0.05       0  5003.8    0.05       0
Bank Sta=4970.9,5003.8
Exp/Cntr=0.3,0.1

Type RM Length L Ch R = 1,39711,763,763,763
BEGIN DESCRIPTION:
Deadman Creek 37.0
END DESCRIPTION:
XS GIS Cut Line= 3
      1621955.02      6917788.02      1623155.00      6919388.00
      1623655.01      6919588.00
#Sta/Elev= 30
  3000.1 1653.57  3136.5 1649.61  3171.9 1647.07  3328.2 1640.70  3350.1 1638.53
  3450.1 1634.74  3571.9 1622.35  3657.4 1619.09  3863.6 1615.01  4386.5 1610.11
  4457.4 1608.23  4557.4 1611.35  4909.7 1610.92  4929.3 1610.52  4942.8 1610.02
  4957.7 1594.76  4958.7 1593.76  5002.6 1593.76  5003.6 1594.76  5009.5 1599.00
  5032.4 1600.61  5039.1 1601.65  5044.5 1604.06  5063.3 1606.97  5068.7 1612.63
  5098.4 1623.56  5183.2 1634.37  5278.8 1638.19  5301.6 1640.55  5538.6 1646.47
#Mann=5,-1,0
  3000.1    0.05       0  4909.7    0.12       0  4929.3    0.05       0
  4957.7    0.05       0  5003.6    0.05       0
Bank Sta=4957.7,5003.6
Exp/Cntr=0.3,0.1

Type RM Length L Ch R = 1,38948,862,862,862
BEGIN DESCRIPTION:
Mapping XS 338d8178
END DESCRIPTION:
XS GIS Cut Line= 4
      1621826.63      6918429.48      1622139.14      6919179.52
      1622701.64      6919986.81      1623341.11      6919695.67
#Sta/Elev= 30
  3557.0 1632.19  3652.9 1630.34  3698.7 1627.85  3804.9 1615.71  3858.7 1613.61
  4035.6 1611.75  4458.8 1610.56  4667.4 1607.18  4745.5 1609.53  4865.2 1609.06
  4896.8 1607.67  4911.7 1604.21  4917.8 1605.07  4940.5 1600.41  4977.1 1598.25
  4979.1 1594.68  4980.0 1593.68  5017.6 1593.68  5018.5 1594.68  5019.0 1596.48
  5025.8 1604.18  5033.8 1607.70  5062.4 1609.95  5108.4 1609.33  5313.9 1608.77
  5423.1 1606.94  5829.6 1611.30  5891.8 1614.53  5983.5 1627.08  6056.1 1634.55
#Mann=5,-1,0
  3557.0    0.05       0  4865.2    0.12       0  4979.1    0.07       0
  5018.5    0.12       0  5108.4    0.05       0
Bank Sta=4979.1,5018.5
Exp/Cntr=0.3,0.1

Type RM Length L Ch R = 1,38086,476,476,476
BEGIN DESCRIPTION:
Mapping XS 6e2b7662
END DESCRIPTION:
XS GIS Cut Line= 3
      1621363.08      6919986.80      1622378.73      6920200.35
      1623368.29      6919715.98
#Sta/Elev= 30
  4583.0 1635.85  4799.6 1631.87  4881.3 1625.98  4900.7 1622.13  4905.8 1622.73
  4942.6 1612.97  4950.5 1607.64  4955.6 1608.92  4973.3 1597.78  4976.4 1594.53
  4977.6 1593.53  5028.0 1593.53  5029.2 1594.53  5034.6 1600.01  5050.2 1606.17
  5077.6 1606.58  5235.1 1607.81  5388.9 1609.98  5588.3 1606.06  5716.9 1608.67
  5888.6 1609.01  6046.2 1606.86  6479.4 1610.86  6546.9 1613.29  6552.5 1614.94
  6585.3 1618.79  6607.6 1623.68  6636.9 1627.45  6681.9 1632.92  6722.6 1635.69
#Mann=5,-1,0
  4583.0    0.05       0  4976.4    0.05       0  5029.2    0.05       0
  5077.6    0.12       0  5235.1    0.05       0
Bank Sta=4976.4,5029.2
Exp/Cntr=0.3,0.1

Type RM Length L Ch R = 1,37610,705,705,705
BEGIN DESCRIPTION:
Deadman Creek 36.0
END DESCRIPTION:
XS GIS Cut Line= 3
      1621455.02      6920488.00      1621955.00      6920488.00
      1623554.97      6919688.02
#Sta/Elev= 30
  4505.6 1640.44  4805.6 1633.04  4855.6 1629.47  4865.6 1628.42  4875.6 1624.69
  4915.6 1614.39  4925.6 1610.58  4955.1 1594.41  4956.4 1593.41  5013.1 1593.41
  5014.5 1594.41  5019.6 1602.31  5036.3 1605.64  5050.1 1606.47  5076.5 1605.97
  5220.8 1607.65  5304.7 1605.77  5452.8 1605.85  5729.5 1610.05  5891.6 1607.00
  5936.3 1607.13  6400.3 1610.78  6428.3 1612.88  6445.1 1612.32  6467.4 1613.87
  6526.1 1626.34  6579.2 1633.35  6646.3 1640.04  6713.4 1645.11  6794.4 1647.28
#Mann=5,-1,0
  4505.6    0.05       0  4955.1    0.05       0  5014.5    0.05       0
  5050.1    0.12       0  5076.5    0.05       0
Bank Sta=4955.1,5014.5
Exp/Cntr=0.3,0.1

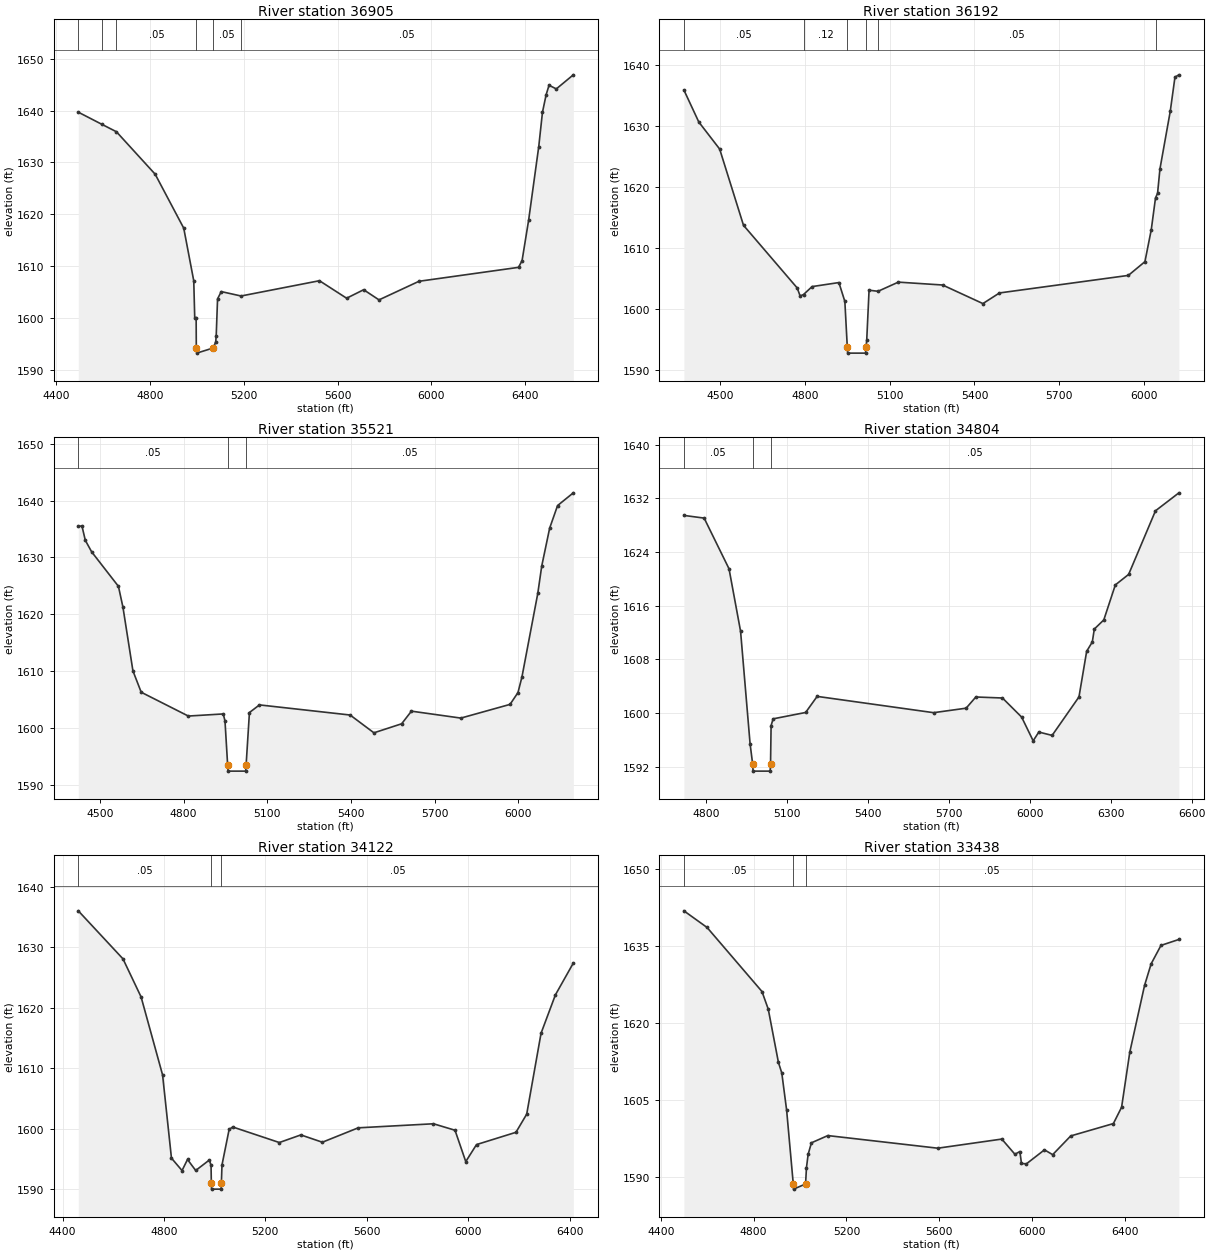
Type RM Length L Ch R = 1,36905,713,713,713
BEGIN DESCRIPTION:
Deadman Creek 35.0
END DESCRIPTION:
XS GIS Cut Line= 3
      1622105.00      6921387.99      1622405.00      6920988.00
      1623804.96      6920188.02
#Sta/Elev= 30
  4493.3 1639.69  4595.4 1637.31  4656.0 1635.91  4821.4 1627.71  4943.3 1617.29
  4986.0 1607.13  4990.2 1599.92  4996.2 1599.92  4996.9 1594.17  4998.6 1593.17
  5069.6 1594.17  5079.7 1595.34  5081.8 1596.51  5087.6 1603.65  5103.4 1605.05
  5187.8 1604.20  5522.4 1607.15  5638.3 1603.77  5711.0 1605.41  5776.5 1603.45
  5947.1 1607.04  6371.8 1609.73  6386.9 1611.01  6415.0 1618.85  6458.2 1633.06
  6474.0 1639.67  6489.8 1643.08  6502.1 1644.89  6533.0 1644.18  6605.7 1646.90
#Mann=6,-1,0
  4493.3    0.05       0  4595.4    0.12       0  4656.0    0.05       0
  4996.9    0.05       0  5069.6    0.05       0  5187.8    0.05       0
Bank Sta=4996.9,5069.6
Exp/Cntr=0.3,0.1

Type RM Length L Ch R = 1,36192,671,671,671
BEGIN DESCRIPTION:
Deadman Creek 34.0
END DESCRIPTION:
XS GIS Cut Line= 3
      1622354.98      6921588.01      1622955.00      6921388.00
      1623954.99      6920888.00
#Sta/Elev= 30
  4372.5 1635.87  4425.2 1630.63  4499.0 1626.20  4583.3 1613.72  4773.1 1603.47
  4783.6 1602.15  4795.5 1602.39  4825.8 1603.69  4920.6 1604.35  4941.7 1601.26
  4950.3 1593.80  4951.8 1592.80  5014.9 1592.80  5016.4 1593.80  5019.0 1594.89
  5027.3 1603.10  5059.0 1602.92  5130.8 1604.42  5287.3 1603.95  5429.8 1600.91
  5488.5 1602.65  5944.1 1605.52  6002.8 1607.77  6025.2 1613.00  6040.2 1618.20
  6047.5 1618.96  6055.9 1622.95  6092.3 1632.37  6109.0 1637.97  6123.0 1638.35
#Mann=6,-1,0
  4372.5    0.05       0  4795.5    0.12       0  4950.3    0.07       0
  5016.4    0.12       0  5059.0    0.05       0  6040.2    0.12       0
Bank Sta=4950.3,5016.4
Exp/Cntr=0.3,0.1

Type RM Length L Ch R = 1,35521,717,717,717
BEGIN DESCRIPTION:
Deadman Creek 33.0
END DESCRIPTION:
XS GIS Cut Line= 3
      1622702.83      6922261.50      1623205.00      6921988.00
      1624105.02      6921187.99
#Sta/Elev= 30
  4421.9 1635.44  4434.9 1635.55  4447.1 1633.00  4469.9 1630.97  4565.9 1624.91
  4582.1 1621.24  4617.9 1610.04  4647.6 1606.28  4816.6 1602.09  4942.0 1602.46
  4948.2 1601.22  4957.8 1593.40  4959.3 1592.40  5022.4 1592.40  5023.9 1593.40
  5035.9 1602.71  5071.9 1604.05  5397.2 1602.27  5482.5 1599.14  5582.0 1600.73
  5617.1 1602.95  5794.4 1601.73  5970.8 1604.14  5999.3 1606.22  6013.5 1608.95
  6070.4 1623.67  6084.6 1628.49  6113.0 1635.15  6141.4 1639.12  6197.9 1641.36
#Mann=3,-1,0
  4421.9    0.05       0  4957.8    0.03       0  5023.9    0.05       0
Bank Sta=4957.8,5023.9
Exp/Cntr=0.3,0.1

Type RM Length L Ch R = 1,34804,682,682,682
BEGIN DESCRIPTION:
Deadman Creek 32.0
END DESCRIPTION:
XS GIS Cut Line= 3
      1623191.22      6922820.15      1623405.00      6922638.00
      1624566.23      6921606.60
#Sta/Elev= 30
  4718.9 1629.47  4793.9 1629.07  4886.1 1621.51  4928.9 1612.19  4964.1 1595.42
  4973.8 1592.32  4975.3 1591.32  5038.4 1591.32  5039.9 1592.32  5042.0 1598.12
  5049.5 1599.12  5169.9 1600.07  5212.6 1602.47  5644.1 1600.04  5764.5 1600.71
  5800.5 1602.38  5899.2 1602.23  5970.2 1599.38  6012.9 1595.84  6033.8 1597.15
  6083.1 1596.65  6182.6 1602.39  6211.1 1609.20  6232.0 1610.59  6239.5 1612.52
  6274.6 1613.88  6317.3 1619.10  6366.6 1620.67  6466.1 1630.16  6552.9 1632.84
#Mann=3,-1,0
  4718.9    0.05       0  4973.8    0.05       0  5039.9    0.05       0
Bank Sta=4973.8,5039.9
Exp/Cntr=0.3,0.1

Type RM Length L Ch R = 1,34122,684,684,684
BEGIN DESCRIPTION:
Deadman Creek 31.0
END DESCRIPTION:
XS GIS Cut Line= 3
      1623705.02      6923587.95      1623905.00      6923088.00
      1624905.01      6922087.99
#Sta/Elev= 30
  4462.1 1636.04  4638.4 1628.10  4709.8 1621.81  4794.6 1608.92  4829.6 1595.17
  4871.3 1593.12  4892.9 1594.95  4925.2 1593.13  4979.0 1594.86  4985.8 1593.98
  4986.9 1591.05  4987.8 1590.05  5025.6 1590.05  5026.5 1591.05  5028.9 1594.04
  5057.1 1599.91  5071.3 1600.32  5255.1 1597.75  5340.0 1599.01  5424.8 1597.80
  5566.3 1600.18  5863.2 1600.85  5948.1 1599.78  5990.5 1594.60  6032.9 1597.41
  6188.5 1599.44  6230.9 1602.44  6287.5 1615.81  6344.1 1622.15  6414.8 1627.41
#Mann=3,-1,0
  4462.1    0.05       0  4986.9    0.05       0  5026.5    0.05       0
Bank Sta=4986.9,5026.5
Exp/Cntr=0.3,0.1

Type RM Length L Ch R = 1,33438,393,393,393
BEGIN DESCRIPTION:
Deadman Creek 30.0
END DESCRIPTION:
XS GIS Cut Line= 3
      1623855.02      6923937.98      1624255.00      6923638.00
      1625410.61      6922484.30
#Sta/Elev= 30
  4499.6 1641.92  4599.6 1638.67  4836.0 1626.19  4863.1 1622.75  4906.9 1612.37
  4921.4 1610.31  4942.3 1603.04  4970.9 1588.66  4972.1 1587.66  5023.8 1588.66
  5027.8 1591.87  5034.9 1594.43  5049.1 1596.69  5119.8 1598.10  5593.5 1595.64
  5869.3 1597.42  5925.9 1594.46  5947.1 1594.99  5954.2 1592.66  5975.4 1592.59
  6053.2 1595.32  6088.5 1594.38  6166.3 1598.03  6350.1 1600.44  6385.5 1603.63
  6420.9 1614.39  6484.5 1627.39  6512.8 1631.59  6555.2 1635.18  6632.5 1636.34
#Mann=3,-1,0
  4499.6    0.05       0  4970.9    0.05       0  5023.8    0.05       0
Bank Sta=4970.9,5023.8
Exp/Cntr=0.3,0.1

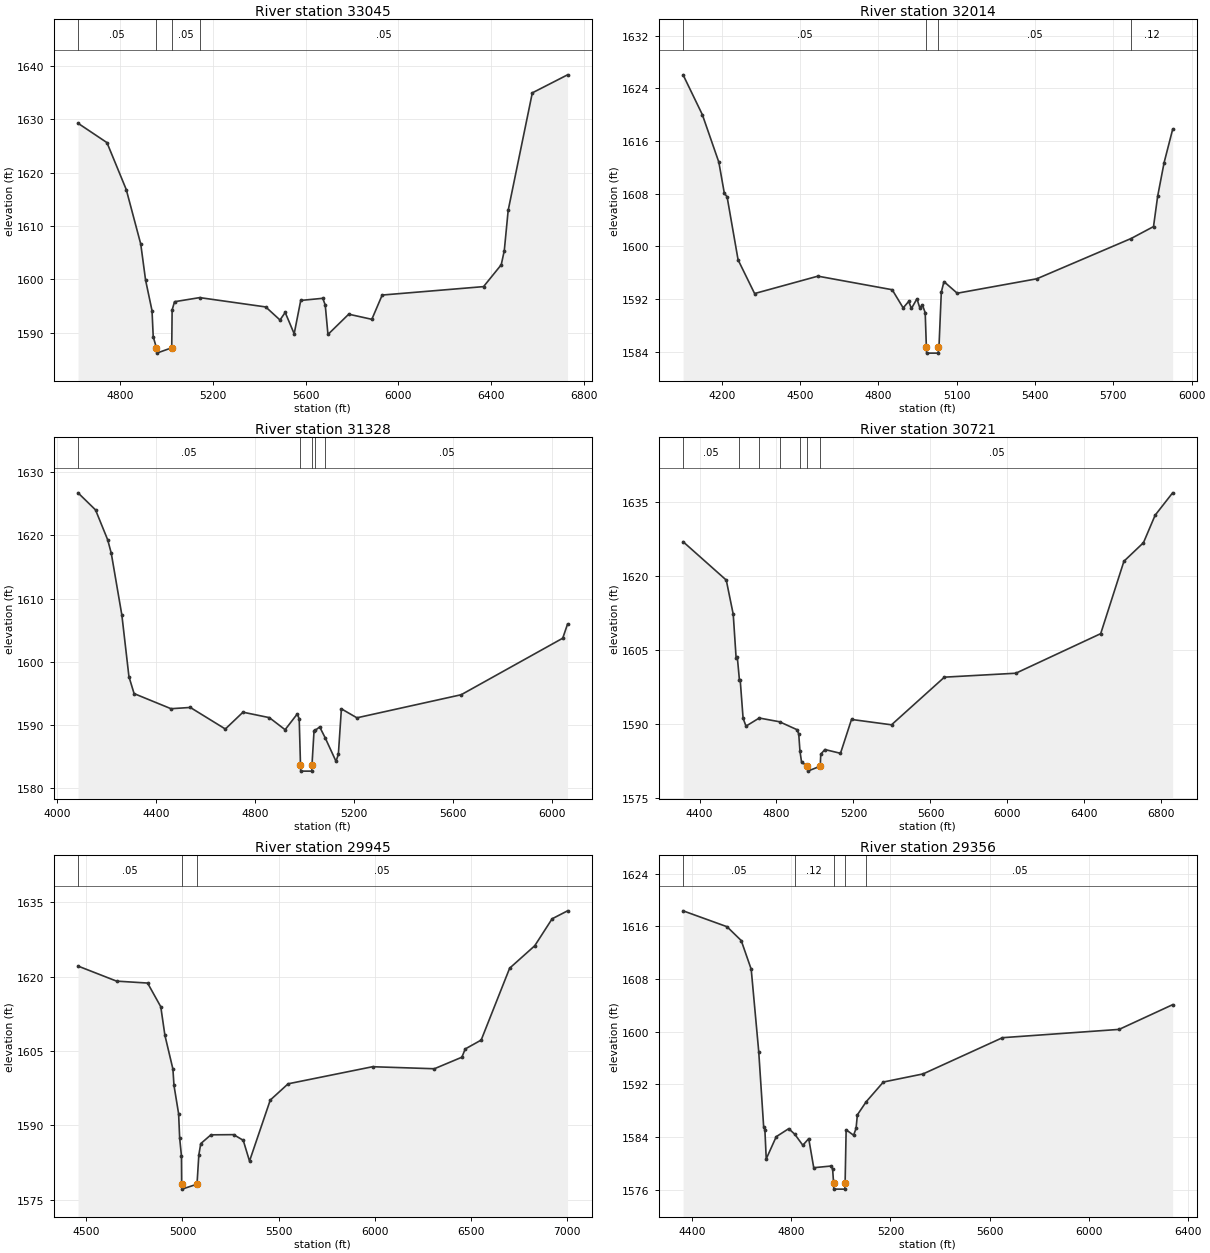
Type RM Length L Ch R = 1,33045,1031,1031,1031
BEGIN DESCRIPTION:
Mapping XS d57202fe
END DESCRIPTION:
XS GIS Cut Line= 3
      1624165.16      6924023.27      1624680.81      6923872.22
      1626091.18      6923169.64
#Sta/Elev= 30
  4617.0 1629.29  4741.9 1625.66  4825.2 1616.86  4887.8 1606.63  4908.6 1599.88
  4936.4 1594.16  4941.6 1589.27  4955.4 1587.19  4956.9 1586.19  5021.5 1587.19
  5023.2 1594.28  5033.6 1595.83  5142.2 1596.60  5427.2 1594.85  5488.8 1592.40
  5511.2 1593.82  5550.0 1589.82  5578.3 1596.07  5673.5 1596.47  5684.1 1595.20
  5695.8 1589.69  5785.4 1593.49  5885.2 1592.53  5929.9 1597.08  6367.4 1598.66
  6443.8 1602.76  6456.9 1605.41  6473.7 1612.96  6577.9 1634.99  6730.0 1638.37
#Mann=4,-1,0
  4617.0    0.05       0  4955.4    0.07       0  5021.5    0.05       0
  5142.2    0.05       0
Bank Sta=4955.4,5021.5
Exp/Cntr=0.3,0.1

Type RM Length L Ch R = 1,32014,686,686,686
BEGIN DESCRIPTION:
Deadman Creek 29.0
END DESCRIPTION:
XS GIS Cut Line= 3
      1624255.03      6924088.01      1625155.00      6924388.00
      1626067.03      6924553.07
#Sta/Elev= 30
  4051.6 1626.06  4125.4 1620.01  4188.6 1612.79  4209.7 1608.05  4220.2 1607.54
  4262.4 1597.95  4325.6 1592.84  4568.1 1595.48  4852.7 1593.42  4894.8 1590.66
  4915.9 1591.64  4926.5 1590.57  4947.5 1592.04  4958.1 1590.72  4968.6 1591.09
  4979.2 1589.93  4983.6 1584.79  4984.6 1583.79  5029.1 1583.79  5030.1 1584.79
  5032.1 1584.82  5040.9 1593.05  5051.1 1594.65  5101.9 1592.89  5406.7 1595.08
  5768.1 1601.20  5853.9 1603.01  5869.8 1607.63  5894.5 1612.73  5927.1 1617.76
#Mann=4,-1,0
  4051.6    0.05       0  4983.6    0.05       0  5030.1    0.05       0
  5768.1    0.12       0
Bank Sta=4983.6,5030.1
Exp/Cntr=0.3,0.1

Type RM Length L Ch R = 1,31328,607,607,607
BEGIN DESCRIPTION:
Deadman Creek 28.0
END DESCRIPTION:
XS GIS Cut Line= 3
      1624105.03      6924288.02      1624805.00      6924888.00
      1625768.89      6925320.53
#Sta/Elev= 30
  4083.3 1626.72  4154.1 1624.02  4203.4 1619.27  4217.7 1617.16  4260.5 1607.38
  4289.1 1597.65  4309.9 1594.97  4459.2 1592.58  4537.1 1592.78  4678.7 1589.37
  4750.0 1592.03  4856.5 1591.17  4920.2 1589.26  4969.5 1591.76  4977.2 1590.97
  4982.4 1583.71  4983.4 1582.71  5027.9 1582.71  5028.9 1583.71  5037.2 1589.12
  5042.1 1589.17  5060.0 1589.70  5082.4 1587.96  5125.8 1584.27  5135.4 1585.34
  5147.7 1592.56  5210.4 1591.14  5631.8 1594.79  6042.2 1603.73  6061.7 1605.97
#Mann=5,-1,0
  4083.3    0.05       0  4982.4    0.05       0  5028.9    0.05       0
  5042.1    0.12       0  5082.4    0.05       0
Bank Sta=4982.4,5028.9
Exp/Cntr=0.3,0.1

Type RM Length L Ch R = 1,30721,776,776,776
BEGIN DESCRIPTION:
Deadman Creek 27.0
END DESCRIPTION:
XS GIS Cut Line= 3
      1623800.59      6924840.96      1624956.85      6925601.39
      1626104.98      6925438.00
#Sta/Elev= 30
  4314.7 1627.01  4539.1 1619.21  4575.3 1612.26  4590.3 1603.36  4596.3 1603.64
  4607.4 1598.93  4611.4 1598.96  4626.5 1591.14  4641.6 1589.54  4710.4 1591.19
  4815.7 1590.43  4906.6 1588.82  4915.7 1587.94  4921.8 1584.52  4930.4 1582.21
  4960.7 1581.40  4962.2 1580.40  5027.3 1581.40  5030.1 1583.83  5051.2 1584.79
  5132.6 1584.02  5189.8 1590.90  5397.7 1589.81  5672.5 1599.49  6043.6 1600.29
  6484.6 1608.33  6605.3 1623.04  6706.8 1626.81  6767.4 1632.39  6858.3 1636.94
#Mann=7,-1,0
  4314.7    0.05       0  4607.4    0.12       0  4710.4    0.05       0
  4815.7    0.12       0  4921.8    0.05       0  4960.7    0.05       0
  5027.3    0.05       0
Bank Sta=4960.7,5027.3
Exp/Cntr=0.3,0.1

Type RM Length L Ch R = 1,29945,589,589,589
BEGIN DESCRIPTION:
Deadman Creek 26.0
END DESCRIPTION:
XS GIS Cut Line= 3
      1623754.99      6925237.98      1623955.00      6925738.00
      1625954.99      6925938.00
#Sta/Elev= 30
  4456.2 1622.14  4656.8 1619.10  4818.4 1618.71  4887.0 1613.93  4908.6 1608.15
  4950.3 1601.33  4955.7 1598.07  4979.9 1592.33  4985.3 1587.45  4994.7 1583.78
  4995.8 1578.11  4997.6 1577.11  5075.7 1578.11  5085.2 1584.03  5095.2 1586.30
  5148.0 1588.07  5266.1 1588.11  5316.3 1586.97  5349.0 1582.77  5457.0 1595.09
  5550.0 1598.37  5989.7 1601.82  6311.3 1601.41  6454.5 1603.74  6472.1 1605.41
  6555.0 1607.20  6703.2 1621.71  6833.9 1626.24  6924.3 1631.68  7004.7 1633.29
#Mann=3,-1,0
  4456.2    0.05       0  4995.8    0.05       0  5075.7    0.05       0
Bank Sta=4995.8,5075.7
Exp/Cntr=0.3,0.1

Type RM Length L Ch R = 1,29356,847,847,847
BEGIN DESCRIPTION:
Mapping XS 781b8b91
END DESCRIPTION:
XS GIS Cut Line= 3
      1623472.46      6926200.35      1624071.44      6926278.47
      1625440.57      6926340.94
#Sta/Elev= 30
  4363.7 1618.36  4540.8 1615.95  4598.2 1613.85  4638.5 1609.49  4668.8 1597.00
  4688.7 1585.57  4693.7 1585.10  4699.1 1580.70  4739.4 1584.07  4789.8 1585.29
  4814.5 1584.43  4846.7 1582.77  4870.5 1583.78  4890.7 1579.36  4961.3 1579.62
  4967.0 1579.11  4970.6 1577.11  4971.7 1576.11  5016.2 1576.11  5017.3 1577.11
  5021.4 1585.12  5051.4 1584.29  5061.4 1585.32  5066.7 1587.39  5102.4 1589.38
  5171.5 1592.37  5331.7 1593.60  5652.0 1599.10  6122.5 1600.36  6338.3 1604.11
#Mann=5,-1,0
  4363.7    0.05       0  4814.5    0.12       0  4970.6    0.07       0
  5017.3    0.12       0  5102.4    0.05       0
Bank Sta=4970.6,5017.3
Exp/Cntr=0.3,0.1

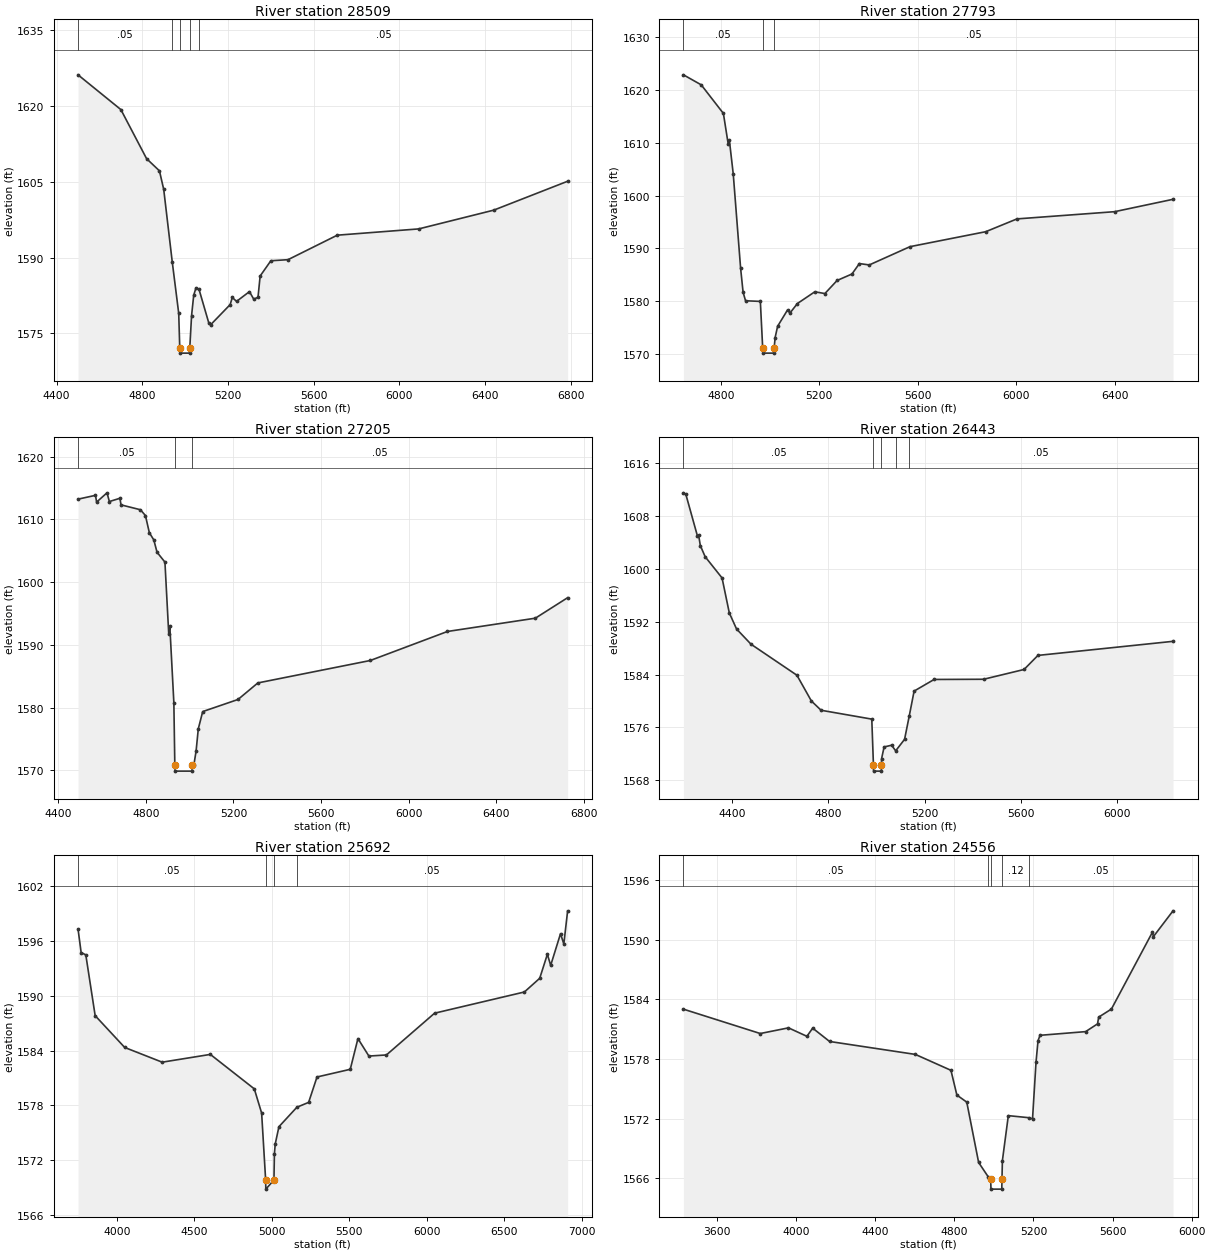
Type RM Length L Ch R = 1,28509,716,716,716
BEGIN DESCRIPTION:
Deadman Creek 25.0
END DESCRIPTION:
XS GIS Cut Line= 3
      1623255.01      6926938.00      1623755.00      6926938.00
      1625540.11      6926939.93
#Sta/Elev= 30
  4500.2 1626.15  4700.2 1619.27  4820.2 1609.56  4880.2 1607.15  4900.2 1603.47
  4939.8 1589.19  4970.2 1578.94  4975.0 1572.08  4976.1 1571.08  5020.7 1571.08
  5021.8 1572.08  5030.2 1578.52  5040.2 1582.54  5050.2 1583.93  5064.9 1583.70
  5110.2 1577.10  5120.2 1576.74  5210.2 1580.68  5220.2 1582.09  5240.2 1581.32
  5300.2 1583.25  5320.2 1581.77  5340.2 1582.12  5350.2 1586.34  5400.2 1589.36
  5480.2 1589.57  5710.2 1594.42  6090.2 1595.66  6440.2 1599.37  6785.3 1605.09
#Mann=5,-1,0
  4500.2    0.05       0  4939.8    0.12       0  4975.0    0.07       0
  5021.8    0.12       0  5064.9    0.05       0
Bank Sta=4975,5021.8
Exp/Cntr=0.3,0.1

Type RM Length L Ch R = 1,27793,588,588,588
BEGIN DESCRIPTION:
Deadman Creek 24.0
END DESCRIPTION:
XS GIS Cut Line= 3
      1623352.69      6927627.43      1623705.00      6927638.00
      1625330.95      6927450.45
#Sta/Elev= 30
  4648.0 1622.91  4720.3 1621.01  4810.4 1615.58  4829.6 1609.87  4834.6 1610.51
  4850.4 1604.09  4880.4 1586.16  4890.4 1581.64  4900.4 1580.02  4960.5 1579.90
  4970.0 1571.08  4971.0 1570.08  5015.7 1570.08  5016.7 1571.08  5020.6 1573.04
  5030.7 1575.18  5070.9 1578.27  5081.0 1577.70  5111.2 1579.50  5181.7 1581.72
  5222.8 1581.39  5272.3 1583.87  5332.7 1585.10  5362.9 1587.08  5403.1 1586.82
  5568.5 1590.29  5876.2 1593.13  6003.1 1595.56  6399.7 1596.93  6637.2 1599.28
#Mann=3,-1,0
  4648.0    0.05       0  4970.0    0.05       0  5016.7    0.05       0
Bank Sta=4970,5016.7
Exp/Cntr=0.3,0.1

Type RM Length L Ch R = 1,27205,762,762,762
BEGIN DESCRIPTION:
Deadman Creek 23.0
END DESCRIPTION:
XS GIS Cut Line= 3
      1623254.97      6928087.99      1623765.37      6928181.62
      1625470.15      6927997.60
#Sta/Elev= 30
  4491.2 1613.24  4570.9 1613.85  4576.0 1612.77  4623.4 1614.25  4634.2 1612.86
  4682.3 1613.38  4687.4 1612.33  4775.9 1611.55  4798.7 1610.63  4816.6 1607.88
  4836.9 1606.74  4851.8 1604.76  4887.7 1603.20  4905.0 1591.79  4910.0 1592.97
  4928.4 1580.77  4932.8 1570.85  4934.6 1569.85  5011.2 1569.85  5013.0 1570.85
  5019.8 1570.85  5029.9 1573.07  5039.9 1576.60  5060.0 1579.35  5221.0 1581.28
  5311.5 1583.92  5824.5 1587.50  6176.5 1592.13  6577.6 1594.25  6724.8 1597.52
#Mann=3,-1,0
  4491.2    0.05       0  4932.8    0.03       0  5013.0    0.05       0
Bank Sta=4932.8,5013
Exp/Cntr=0.3,0.1

Type RM Length L Ch R = 1,26443,751,751,751
BEGIN DESCRIPTION:
Deadman Creek 22.0
END DESCRIPTION:
XS GIS Cut Line= 3
      1623205.03      6928788.00      1624004.55      6928853.47
      1625191.19      6928522.25
#Sta/Elev= 30
  4197.8 1611.49  4207.8 1611.27  4256.0 1604.96  4261.0 1605.07  4268.0 1603.51
  4288.1 1601.82  4358.3 1598.61  4388.4 1593.32  4418.5 1590.89  4478.7 1588.58
  4669.3 1583.89  4729.5 1579.99  4769.7 1578.59  4980.4 1577.25  4987.2 1570.38
  4987.9 1569.38  5019.9 1569.38  5020.6 1570.38  5021.2 1571.29  5031.6 1573.04
  5062.8 1573.30  5079.6 1572.45  5116.6 1574.19  5135.8 1577.68  5156.2 1581.49
  5239.3 1583.25  5444.9 1583.28  5613.0 1584.76  5670.7 1586.89  6232.0 1589.02
#Mann=5,-1,0
  4197.8    0.05       0  4987.2    0.03       0  5020.6    0.05       0
  5079.6    0.12       0  5135.8    0.05       0
Bank Sta=4987.2,5020.6
Exp/Cntr=0.3,0.1

Type RM Length L Ch R = 1,25692,1136,1136,1136
BEGIN DESCRIPTION:
Mapping XS ee6747b9
END DESCRIPTION:
XS GIS Cut Line= 4
      1623055.04      6929588.01      1623838.29      6929678.15
      1624570.93      6929372.59      1625700.79      6928268.89
#Sta/Elev= 30
  3748.6 1597.31  3768.7 1594.73  3798.9 1594.47  3859.3 1587.82  4050.1 1584.34
  4292.1 1582.73  4603.1 1583.58  4886.9 1579.81  4934.3 1577.16  4960.2 1569.84
  4961.4 1568.84  5013.8 1569.84  5016.8 1572.71  5022.2 1573.79  5046.0 1575.67
  5162.0 1577.80  5237.7 1578.33  5291.9 1581.11  5506.6 1581.95  5556.2 1585.31
  5626.9 1583.40  5740.1 1583.52  6051.1 1588.09  6631.1 1590.41  6730.1 1591.91
  6779.5 1594.54  6800.8 1593.32  6864.4 1596.79  6885.7 1595.66  6910.3 1599.29
#Mann=4,-1,0
  3748.6    0.05       0  4960.2    0.07       0  5013.8    0.05       0
  5162.0    0.05       0
Bank Sta=4960.2,5013.8
Exp/Cntr=0.3,0.1

Type RM Length L Ch R = 1,24556,446,446,446
BEGIN DESCRIPTION:
Mapping XS 4835d99b
END DESCRIPTION:
XS GIS Cut Line= 4
      1623348.73      6929830.94      1624227.18      6930483.70
      1624897.32      6930497.59      1625605.69      6930445.51
#Sta/Elev= 30
  3430.9 1583.01  3819.3 1580.56  3962.0 1581.13  4055.1 1580.28  4084.3 1581.10
  4169.8 1579.76  4603.2 1578.46  4783.2 1576.86  4813.2 1574.37  4863.2 1573.66
  4923.2 1567.59  4972.9 1566.11  4984.3 1565.91  4985.4 1564.91  5040.2 1564.91
  5041.2 1565.91  5043.3 1567.78  5073.3 1572.30  5179.0 1572.09  5195.6 1571.97
  5213.3 1577.68  5223.4 1579.83  5233.4 1580.38  5464.0 1580.75  5524.2 1581.53
  5530.1 1582.21  5594.4 1583.02  5801.8 1590.75  5806.8 1590.31  5905.9 1592.90
#Mann=5,-1,0
  3430.9    0.05       0  4972.9    0.12       0  4984.3    0.07       0
  5041.2    0.12       0  5179.0    0.05       0
Bank Sta=4984.3,5041.2
Exp/Cntr=0.3,0.1

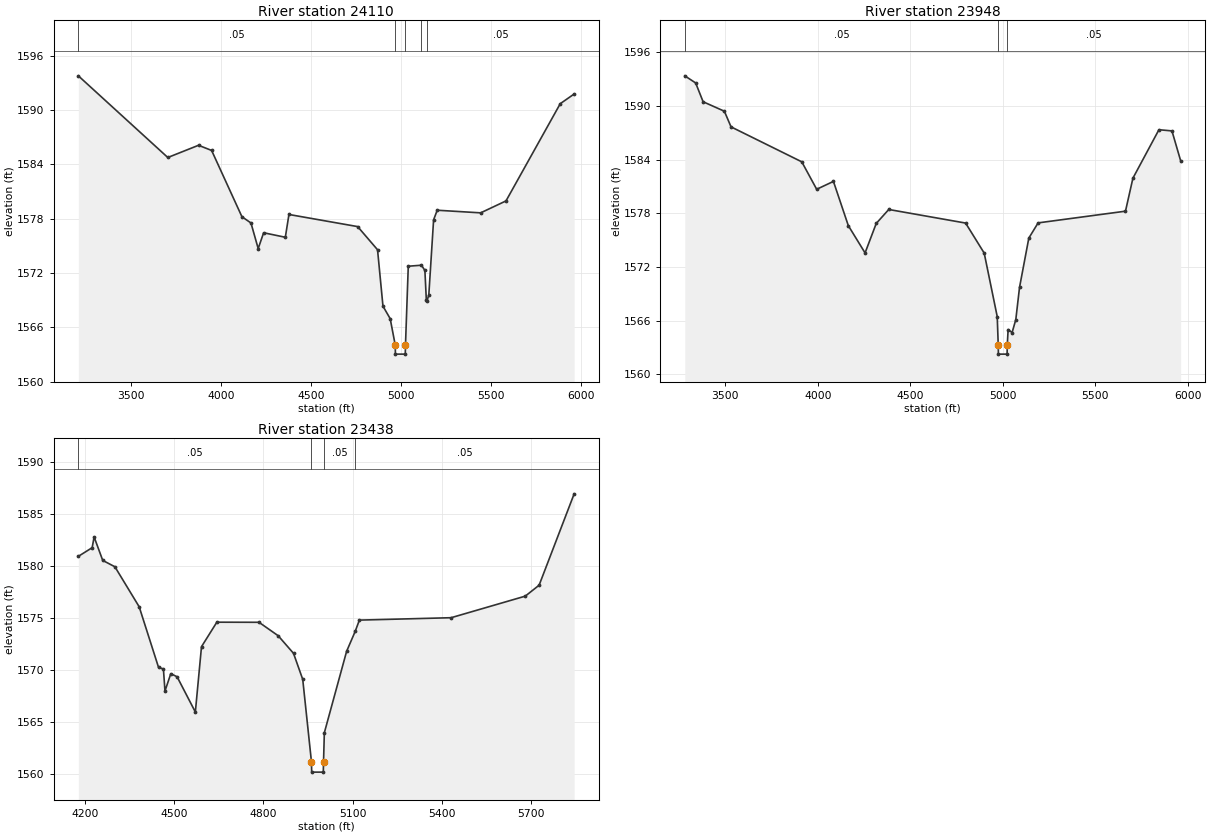
Type RM Length L Ch R = 1,24110,162,162,162
BEGIN DESCRIPTION:
Mapping XS f7fb606b
END DESCRIPTION:
XS GIS Cut Line= 3
      1622970.19      6930719.81      1624886.90      6930910.79
      1625711.59      6931000.88
#Sta/Elev= 30
  3207.4 1593.80  3704.7 1584.77  3875.5 1586.12  3948.2 1585.55  4116.7 1578.22
  4166.9 1577.53  4207.1 1574.70  4237.3 1576.45  4357.9 1575.95  4378.0 1578.47
  4759.9 1577.13  4870.4 1574.57  4900.6 1568.33  4940.7 1566.95  4968.8 1564.03
  4969.8 1563.03  5024.6 1563.03  5025.7 1564.03  5041.2 1572.75  5114.6 1572.86
  5133.6 1572.28  5141.7 1568.96  5145.4 1568.92  5155.4 1569.58  5182.0 1577.88
  5202.1 1578.94  5443.5 1578.65  5584.4 1579.97  5885.9 1590.72  5963.2 1591.79
#Mann=5,-1,0
  3207.4    0.05       0  4968.8    0.05       0  5025.7    0.05       0
  5114.6    0.12       0  5145.4    0.05       0
Bank Sta=4968.8,5025.7
Exp/Cntr=0.3,0.1

Type RM Length L Ch R = 1,23948,510,510,510
BEGIN DESCRIPTION:
Mapping XS d5fdd162
END DESCRIPTION:
XS GIS Cut Line= 3
      1623046.61      6930869.12      1624616.07      6931046.20
      1625711.69      6931153.69
#Sta/Elev= 30
  3281.5 1593.39  3340.3 1592.59  3380.5 1590.49  3495.4 1589.43  3531.5 1587.68
  3913.9 1583.77  3994.4 1580.70  4085.0 1581.58  4165.5 1576.63  4256.0 1573.58
  4316.4 1576.88  4384.1 1578.44  4799.5 1576.92  4900.0 1573.56  4970.4 1566.46
  4975.9 1563.26  4976.8 1562.26  5023.8 1562.26  5024.7 1563.26  5029.3 1565.01
  5050.8 1564.67  5070.9 1566.13  5090.9 1569.72  5141.2 1575.24  5191.4 1576.94
  5663.7 1578.25  5703.9 1581.94  5844.5 1587.36  5914.9 1587.23  5961.8 1583.90
#Mann=3,-1,0
  3281.5    0.05       0  4975.9    0.03       0  5024.7    0.05       0
Bank Sta=4975.9,5024.7
Exp/Cntr=0.3,0.1

Type RM Length L Ch R = 1,23438,534,534,534
BEGIN DESCRIPTION:
Mapping XS 33f22cfc
END DESCRIPTION:
XS GIS Cut Line= 4
      1624053.54      6931744.13      1624841.76      6931542.73
      1625248.01      6931386.48      1625631.68      6931217.11
#Sta/Elev= 30
  4177.3 1580.93  4223.8 1581.76  4230.4 1582.79  4259.4 1580.54  4300.3 1579.93
  4382.0 1576.09  4447.2 1570.27  4463.6 1570.12  4468.8 1568.00  4488.4 1569.67
  4509.6 1569.37  4571.0 1565.99  4591.7 1572.26  4643.3 1574.61  4785.2 1574.60
  4849.7 1573.31  4901.3 1571.62  4932.3 1569.12  4961.6 1561.22  4962.4 1560.22
  5001.5 1560.22  5002.3 1561.22  5005.0 1564.00  5080.0 1571.82  5108.7 1573.72
  5122.9 1574.81  5431.5 1575.04  5681.0 1577.11  5727.6 1578.16  5845.5 1586.93
#Mann=4,-1,0
  4177.3    0.05       0  4961.6    0.05       0  5002.3    0.05       0
  5108.7    0.05       0
Bank Sta=4961.6,5002.3
Exp/Cntr=0.3,0.1