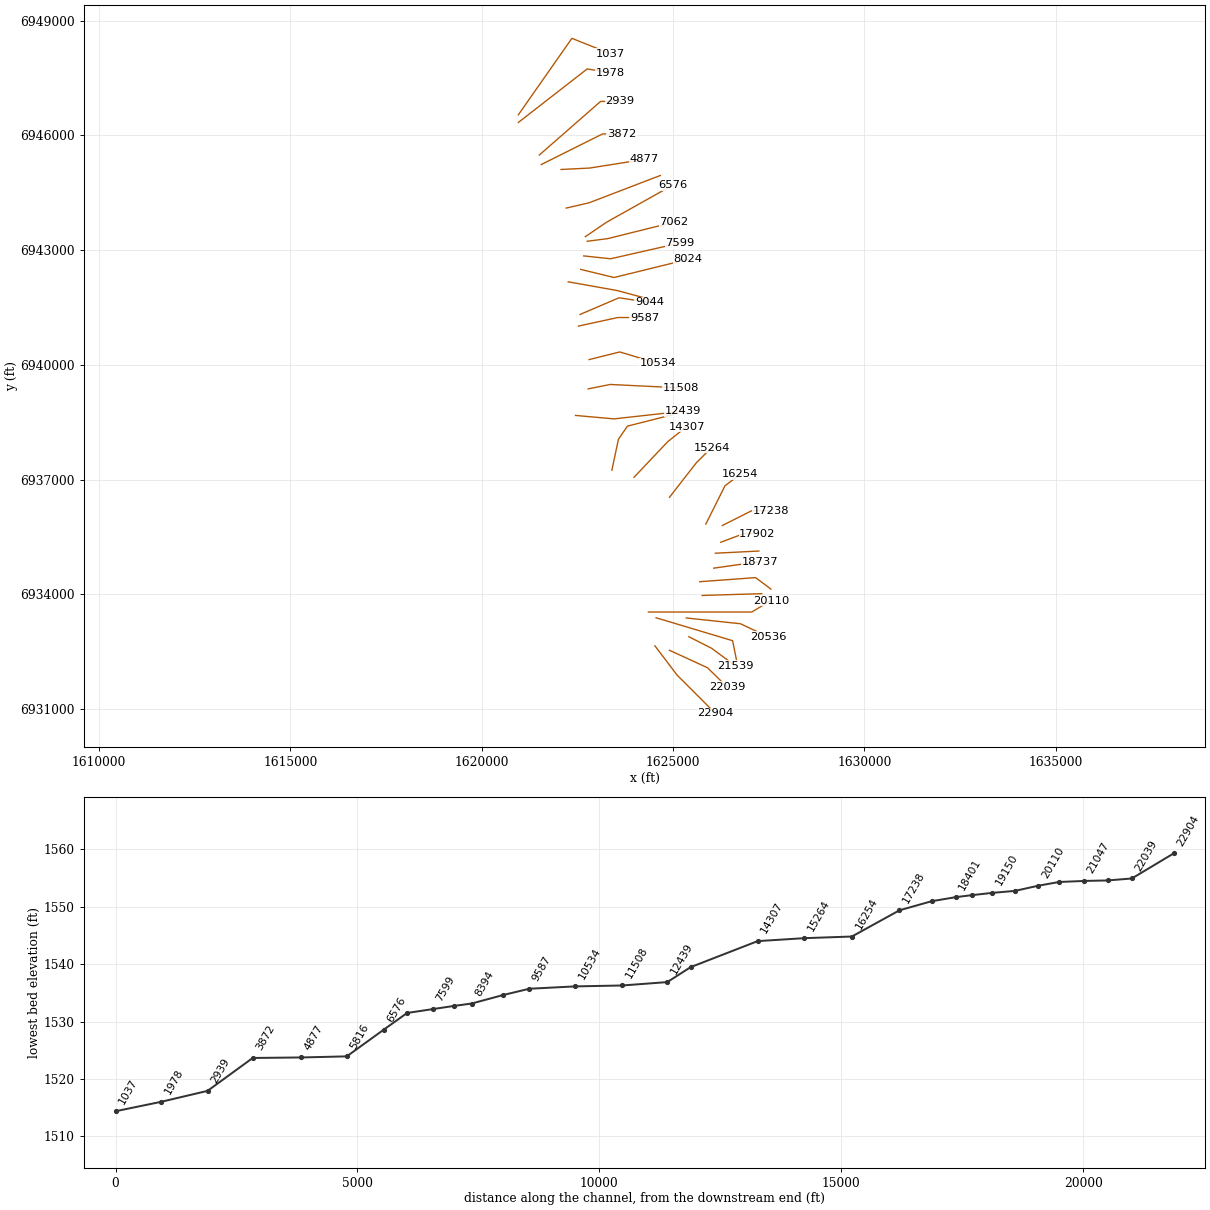
HEC-RAS study Deadman Creek.prj: Deadman Creek Base Level Engineering

--- Deadman Creek.g01 (geometry) --- (continued)

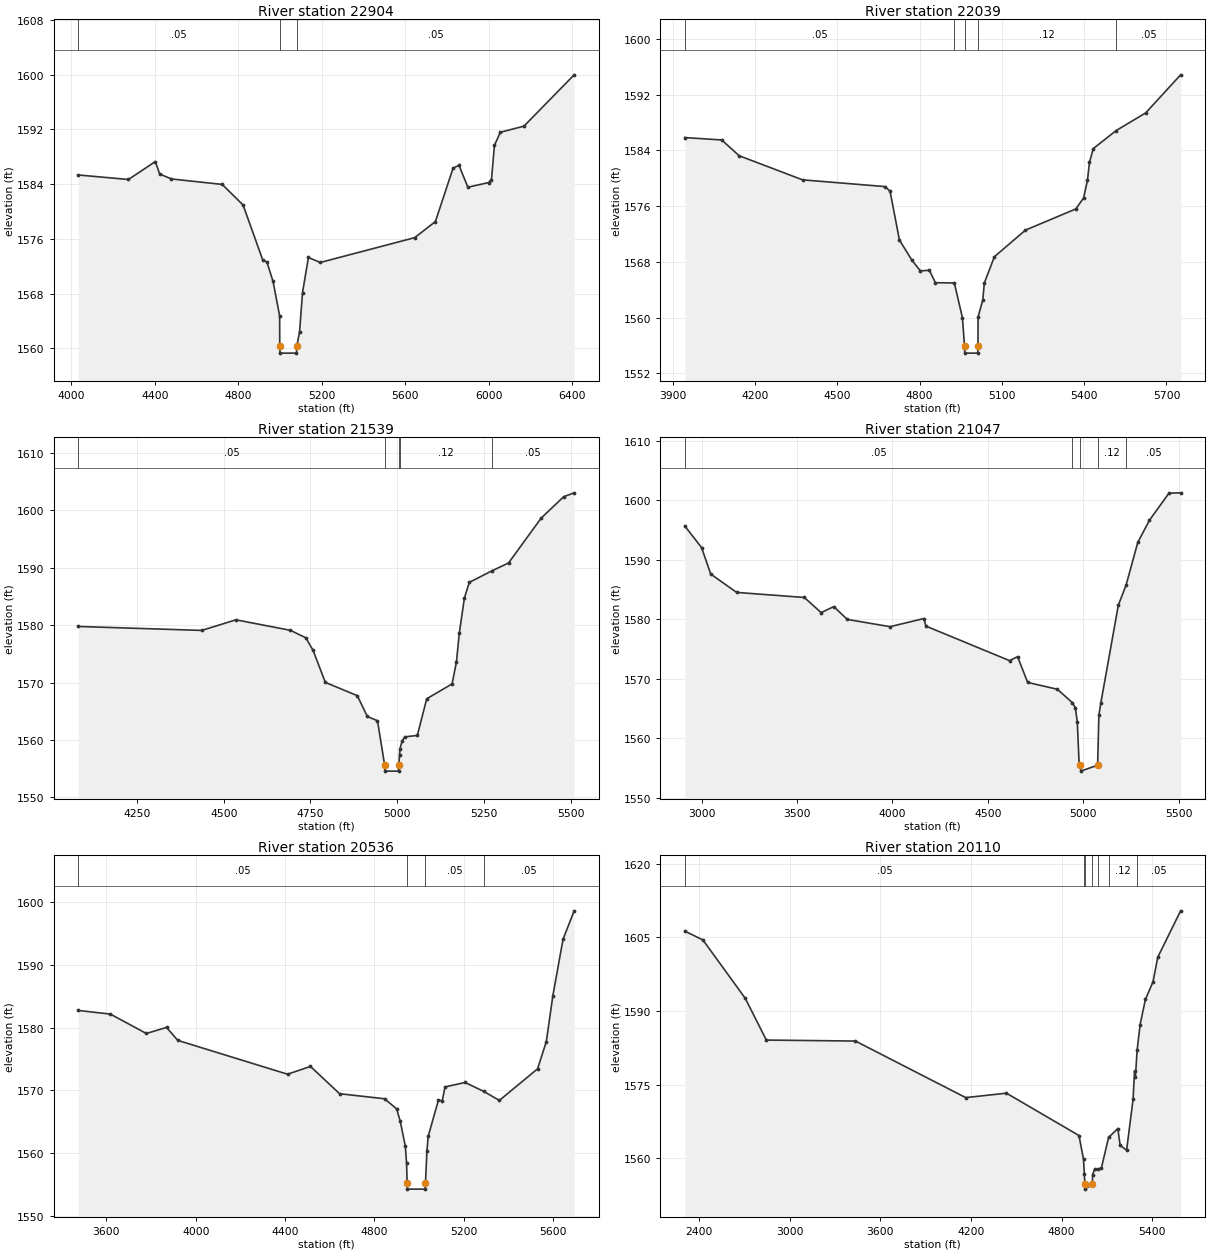
Type RM Length L Ch R = 1,22904,865,865,865
BEGIN DESCRIPTION:
Deadman Creek 21.0
END DESCRIPTION:
XS GIS Cut Line= 3
      1624524.56      6932653.48      1625105.00      6931888.00
      1626105.02      6930887.98
#Sta/Elev= 30
  4034.2 1585.33  4274.1 1584.67  4403.0 1587.29  4423.9 1585.47  4480.3 1584.75
  4723.4 1583.95  4823.3 1580.94  4916.8 1572.97  4937.7 1572.58  4966.8 1569.78
  4998.4 1564.72  4998.9 1560.29  5000.4 1559.29  5079.1 1559.29  5080.6 1560.29
  5093.9 1562.42  5108.0 1568.14  5136.3 1573.27  5192.9 1572.54  5645.4 1576.17
  5744.4 1578.52  5829.2 1586.33  5857.5 1586.74  5900.0 1583.54  5999.0 1584.22
  6013.1 1584.64  6027.2 1589.66  6055.5 1591.57  6168.7 1592.47  6409.1 1599.97
#Mann=3,-1,0
  4034.2    0.05       0  4998.9    0.05       0  5080.6    0.05       0
Bank Sta=4998.9,5080.6
Exp/Cntr=0.3,0.1

Type RM Length L Ch R = 1,22039,500,500,500
BEGIN DESCRIPTION:
Deadman Creek 20.0
END DESCRIPTION:
XS GIS Cut Line= 3
      1624905.00      6932538.00      1625899.56      6932080.56
      1626408.74      6931581.77
#Sta/Elev= 30
  3944.2 1585.83  4078.8 1585.49  4142.2 1583.23  4373.5 1579.77  4675.1 1578.80
  4692.6 1578.12  4726.6 1571.14  4772.5 1568.22  4802.8 1566.72  4835.8 1566.80
  4857.8 1565.02  4926.8 1564.98  4956.3 1559.99  4964.0 1555.92  4964.9 1554.92
  5012.1 1554.92  5013.0 1555.92  5013.3 1560.10  5030.7 1562.58  5036.0 1564.97
  5072.9 1568.75  5186.1 1572.56  5369.8 1575.60  5398.1 1577.18  5412.2 1579.74
  5419.4 1582.28  5433.5 1584.26  5516.8 1586.84  5624.4 1589.37  5751.7 1594.83
#Mann=5,-1,0
  3944.2    0.05       0  4926.8    0.12       0  4964.0    0.07       0
  5013.0    0.12       0  5516.8    0.05       0
Bank Sta=4964,5013
Exp/Cntr=0.3,0.1

Type RM Length L Ch R = 1,21539,492,492,492
BEGIN DESCRIPTION:
Mapping XS 27ff18a6
END DESCRIPTION:
XS GIS Cut Line= 3
      1625409.99      6932893.05      1626003.73      6932590.97
      1626618.29      6932137.87
#Sta/Elev= 30
  4080.6 1579.77  4436.6 1579.08  4535.0 1580.93  4692.1 1579.10  4736.8 1577.79
  4757.4 1575.61  4792.9 1570.03  4885.0 1567.72  4914.0 1564.10  4943.2 1563.35
  4964.0 1555.58  4964.7 1554.58  5004.1 1554.58  5004.8 1555.58  5006.8 1557.39
  5008.0 1558.47  5014.2 1559.82  5021.7 1560.54  5058.1 1560.80  5085.2 1567.18
  5158.3 1569.77  5170.8 1573.55  5179.2 1578.65  5193.9 1584.74  5208.0 1587.45
  5272.4 1589.43  5321.2 1590.83  5415.2 1598.64  5480.0 1602.36  5510.3 1603.04
#Mann=5,-1,0
  4080.6    0.05       0  4964.0    0.03       0  5004.8    0.05       0
  5006.8    0.12       0  5272.4    0.05       0
Bank Sta=4964,5004.8
Exp/Cntr=0.3,0.1

Type RM Length L Ch R = 1,21047,511,511,511
BEGIN DESCRIPTION:
Deadman Creek 19.0
END DESCRIPTION:
XS GIS Cut Line= 3
      1624554.99      6933388.00      1626555.00      6932788.00
      1626655.01      6932287.97
#Sta/Elev= 30
  2911.9 1595.69  2999.8 1592.07  3047.6 1587.62  3183.4 1584.53  3538.3 1583.68
  3626.2 1581.14  3692.3 1582.14  3763.7 1579.99  3987.3 1578.77  4164.7 1580.14
  4175.2 1578.87  4613.7 1573.06  4655.4 1573.73  4708.5 1569.40  4864.2 1568.25
  4942.4 1566.00  4958.2 1565.15  4968.6 1562.74  4978.2 1555.58  4985.2 1555.49
  4986.8 1554.49  5075.0 1555.49  5081.6 1563.86  5091.8 1565.94  5183.5 1582.38
  5224.4 1585.79  5285.5 1592.94  5346.7 1596.67  5448.7 1601.21  5509.9 1601.27
#Mann=5,-1,0
  2911.9    0.05       0  4942.4    0.12       0  4985.2    0.07       0
  5075.0    0.12       0  5224.4    0.05       0
Bank Sta=4985.2,5075
Exp/Cntr=0.3,0.1

Type RM Length L Ch R = 1,20536,426,426,426
BEGIN DESCRIPTION:
Mapping XS da54b854
END DESCRIPTION:
XS GIS Cut Line= 3
      1625342.29      6933382.64      1626758.94      6933231.60
      1627477.72      6932893.04
#Sta/Elev= 30
  3474.7 1582.72  3618.2 1582.14  3779.1 1579.06  3869.6 1580.02  3919.9 1577.96
  4411.1 1572.58  4513.6 1573.82  4644.0 1569.48  4845.1 1568.68  4899.4 1567.07
  4915.6 1565.09  4938.4 1561.10  4943.9 1558.40  4946.2 1555.31  4947.7 1554.31
  5026.9 1554.31  5028.4 1555.31  5035.0 1560.45  5040.6 1562.70  5086.1 1568.42
  5103.4 1568.37  5116.1 1570.56  5205.6 1571.27  5289.5 1569.84  5359.3 1568.42
  5530.2 1573.44  5569.3 1577.77  5598.5 1585.04  5644.1 1594.03  5693.9 1598.56
#Mann=4,-1,0
  3474.7    0.05       0  4946.2    0.07       0  5028.4    0.05       0
  5289.5    0.05       0
Bank Sta=4946.2,5028.4
Exp/Cntr=0.3,0.1

Type RM Length L Ch R = 1,20110,486,486,486
BEGIN DESCRIPTION:
Deadman Creek 18.0
END DESCRIPTION:
XS GIS Cut Line= 3
      1624354.97      6933538.00      1627055.00      6933538.00
      1627554.98      6933837.99
#Sta/Elev= 30
  2304.9 1606.28  2424.9 1604.47  2704.9 1592.59  2844.9 1584.06  3434.9 1583.86
  4164.9 1572.33  4434.9 1573.23  4914.9 1564.60  4944.9 1559.79  4950.5 1556.71
  4954.2 1554.67  4955.1 1553.67  5003.8 1554.67  5004.9 1556.63  5018.5 1557.70
  5043.6 1557.80  5063.2 1557.95  5111.0 1564.21  5172.1 1566.02  5187.6 1562.58
  5230.4 1561.62  5273.2 1572.01  5282.9 1577.70  5288.7 1576.60  5300.0 1582.01
  5319.8 1587.23  5354.8 1592.34  5405.3 1595.95  5436.4 1600.94  5588.0 1610.41
#Mann=7,-1,0
  2304.9    0.05       0  4950.5    0.12       0  4954.2    0.07       0
  5003.8    0.12       0  5043.6    0.05       0  5111.0    0.12       0
  5300.0    0.05       0
Bank Sta=4954.2,5003.8
Exp/Cntr=0.3,0.1

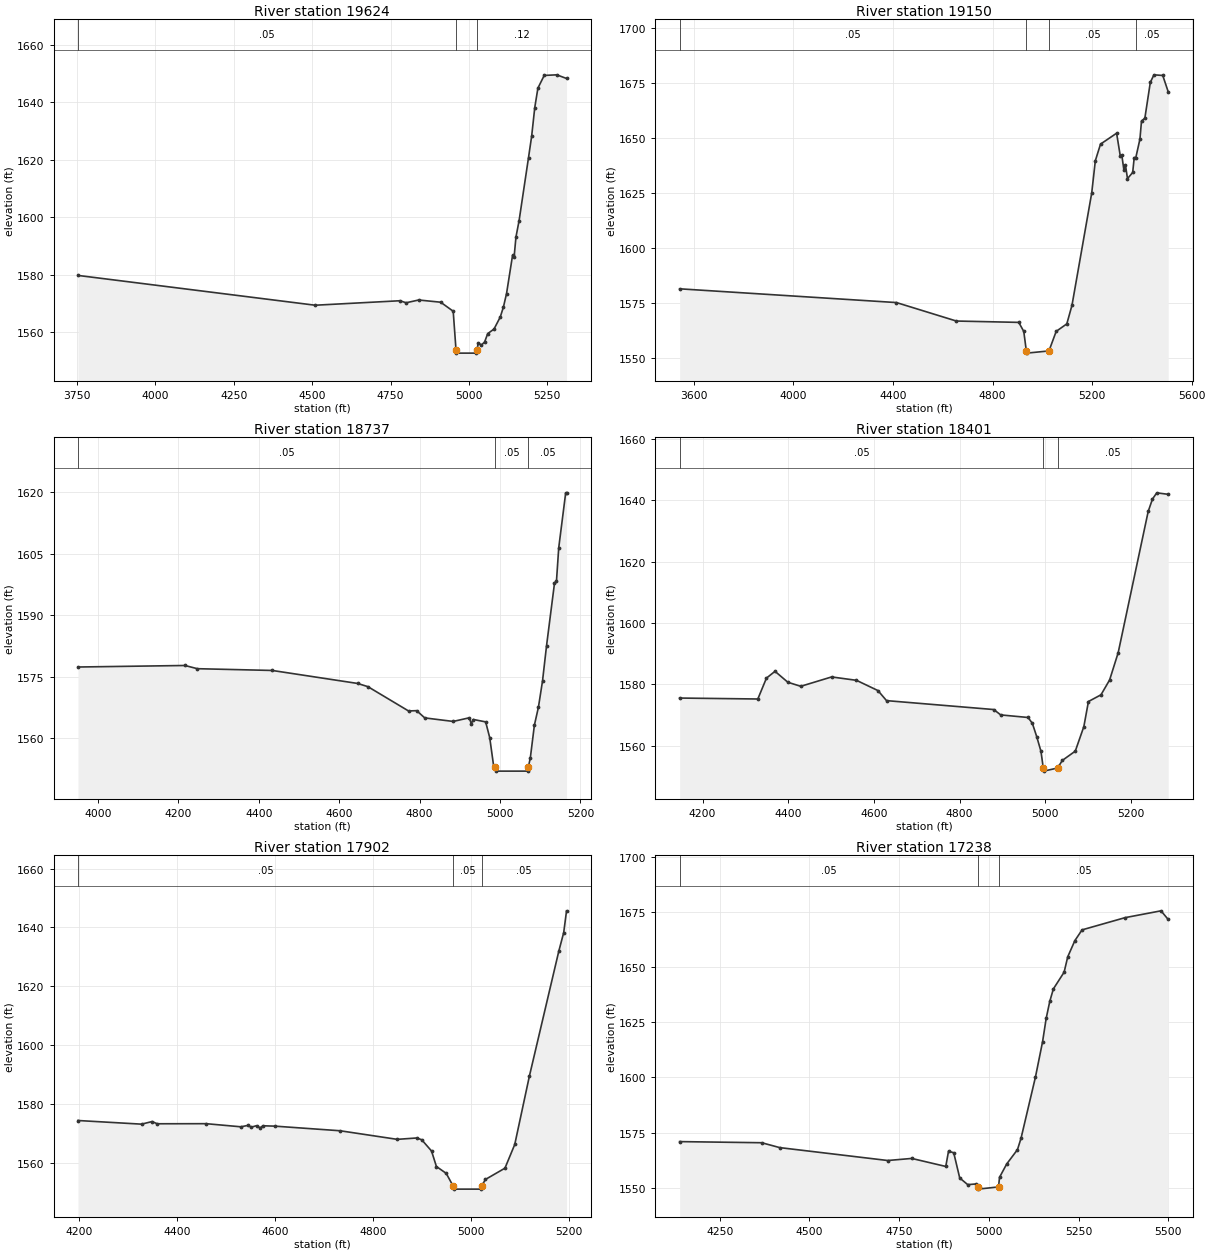
Type RM Length L Ch R = 1,19624,474,474,474
BEGIN DESCRIPTION:
Mapping XS f14ea19e
END DESCRIPTION:
XS GIS Cut Line= 2
      1625758.92      6933971.18      1627316.22      6934018.06
#Sta/Elev= 30
  3753.3 1579.80  4509.7 1569.43  4779.8 1570.99  4799.9 1570.29  4839.9 1571.25
  4909.9 1570.48  4949.9 1567.34  4958.9 1553.76  4960.1 1552.76  5023.8 1552.76
  5025.0 1553.76  5030.0 1556.24  5040.0 1555.60  5050.0 1556.63  5060.0 1559.56
  5080.0 1561.13  5100.0 1565.34  5110.0 1568.78  5120.0 1573.50  5139.1 1586.75
  5144.1 1586.16  5150.0 1593.15  5160.0 1598.87  5190.0 1620.77  5200.0 1628.20
  5210.0 1638.23  5220.0 1644.98  5240.1 1649.40  5280.1 1649.61  5311.3 1648.34
#Mann=3,-1,0
  3753.3    0.05       0  4958.9    0.07       0  5025.0    0.12       0
Bank Sta=4958.9,5025
Exp/Cntr=0.3,0.1

Type RM Length L Ch R = 1,19150,413,413,413
BEGIN DESCRIPTION:
Deadman Creek 17.0
END DESCRIPTION:
XS GIS Cut Line= 3
      1625696.47      6934330.56      1627155.00      6934438.00
      1627555.01      6934137.99
#Sta/Elev= 30
  3543.3 1581.59  4414.2 1575.35  4654.8 1566.97  4905.5 1566.36  4925.6 1562.26
  4935.9 1553.41  4937.5 1552.41  5026.8 1553.41  5055.8 1562.28  5098.5 1565.68
  5119.3 1574.13  5198.5 1625.05  5213.1 1639.73  5233.9 1647.24  5298.5 1652.19
  5313.1 1641.97  5319.3 1642.36  5327.7 1635.55  5333.9 1637.90  5342.2 1631.59
  5363.1 1634.37  5369.3 1641.15  5375.4 1641.00  5392.2 1649.50  5398.5 1657.72
  5412.0 1659.02  5433.9 1675.26  5448.5 1678.68  5483.9 1678.39  5505.8 1670.98
#Mann=4,-1,0
  3543.3    0.05       0  4935.9    0.03       0  5026.8    0.05       0
  5375.4    0.05       0
Bank Sta=4935.9,5026.8
Exp/Cntr=0.3,0.1

Type RM Length L Ch R = 1,18737,336,336,336
BEGIN DESCRIPTION:
Mapping XS 924bfb22
END DESCRIPTION:
XS GIS Cut Line= 2
      1626061.01      6934684.72      1627264.19      6934856.61
#Sta/Elev= 30
  3950.0 1577.37  4216.1 1577.74  4247.0 1576.96  4433.3 1576.53  4645.5 1573.37
  4671.2 1572.59  4772.3 1566.67  4792.5 1566.74  4812.7 1564.98  4883.4 1564.12
  4923.3 1565.00  4928.3 1563.60  4933.9 1564.59  4964.2 1564.01  4974.3 1560.17
  4984.4 1553.03  4987.7 1553.02  4989.2 1552.02  5068.9 1552.02  5070.4 1553.02
  5075.3 1555.22  5085.4 1563.19  5095.5 1567.60  5105.6 1573.93  5115.7 1582.58
  5135.4 1597.73  5140.4 1598.34  5146.0 1606.42  5163.3 1619.78  5165.4 1619.78
#Mann=3,-1,0
  3950.0    0.05       0  4987.7    0.05       0  5070.4    0.05       0
Bank Sta=4987.7,5070.4
Exp/Cntr=0.3,0.1

Type RM Length L Ch R = 1,18401,499,499,499
BEGIN DESCRIPTION:
Mapping XS 2920dccc
END DESCRIPTION:
XS GIS Cut Line= 2
      1626102.70      6935075.35      1627241.66      6935132.56
#Sta/Elev= 30
  4146.6 1575.51  4329.1 1575.20  4349.2 1582.01  4369.2 1584.23  4399.2 1580.66
  4429.3 1579.34  4501.4 1582.40  4559.4 1581.29  4609.5 1577.95  4629.5 1574.67
  4879.8 1571.76  4896.0 1570.01  4959.9 1569.17  4969.9 1567.26  4980.0 1562.95
  4990.0 1558.12  4995.4 1552.67  4996.0 1551.67  5028.6 1552.67  5040.0 1555.18
  5070.1 1558.19  5090.1 1566.21  5100.8 1574.38  5130.1 1576.57  5150.2 1581.41
  5170.2 1590.29  5240.3 1636.40  5250.3 1640.44  5260.3 1642.46  5287.0 1641.97
#Mann=3,-1,0
  4146.6    0.05       0  4995.4    0.05       0  5028.6    0.05       0
Bank Sta=4995.4,5028.6
Exp/Cntr=0.3,0.1

Type RM Length L Ch R = 1,17902,664,664,664
BEGIN DESCRIPTION:
Mapping XS c7bf02cd
END DESCRIPTION:
XS GIS Cut Line= 3
      1626243.34      6935361.82      1626842.27      6935585.77
      1627200.84      6935585.77
#Sta/Elev= 30
  4196.9 1574.30  4326.8 1573.06  4348.3 1573.94  4358.8 1573.19  4458.7 1573.22
  4529.6 1572.16  4544.3 1572.64  4551.0 1572.04  4561.7 1572.54  4569.2 1571.78
  4574.6 1572.51  4599.5 1572.38  4732.5 1570.81  4849.1 1567.89  4889.1 1568.36
  4899.1 1567.75  4919.1 1563.93  4929.1 1558.65  4949.1 1556.33  4963.4 1551.96
  4964.4 1550.96  5020.3 1550.96  5021.4 1551.96  5029.1 1554.24  5069.1 1558.09
  5089.1 1566.14  5119.1 1589.45  5179.1 1631.90  5189.1 1638.21  5194.9 1645.62
#Mann=3,-1,0
  4196.9    0.05       0  4963.4    0.05       0  5021.4    0.05       0
Bank Sta=4963.4,5021.4
Exp/Cntr=0.3,0.1

Type RM Length L Ch R = 1,17238,984,984,984
BEGIN DESCRIPTION:
Deadman Creek 16.0
END DESCRIPTION:
XS GIS Cut Line= 3
      1626286.24      6935799.69      1627055.00      6936188.00
      1627555.04      6936188.00
#Sta/Elev= 30
  4138.3 1570.90  4367.0 1570.39  4417.2 1568.18  4718.1 1562.34  4785.0 1563.28
  4879.8 1559.65  4887.5 1566.56  4902.0 1565.84  4918.7 1554.43  4941.0 1551.41
  4963.3 1551.71  4968.6 1550.38  4969.7 1549.38  5026.8 1550.38  5029.6 1554.72
  5049.6 1560.77  5079.6 1567.27  5089.6 1572.47  5129.6 1600.06  5149.6 1616.19
  5159.6 1626.72  5169.6 1634.41  5179.6 1640.04  5209.6 1647.64  5219.6 1654.57
  5239.6 1661.94  5259.6 1666.79  5379.6 1672.33  5479.6 1675.41  5499.6 1671.49
#Mann=3,-1,0
  4138.3    0.05       0  4968.6    0.05       0  5026.8    0.05       0
Bank Sta=4968.6,5026.8
Exp/Cntr=0.3,0.1

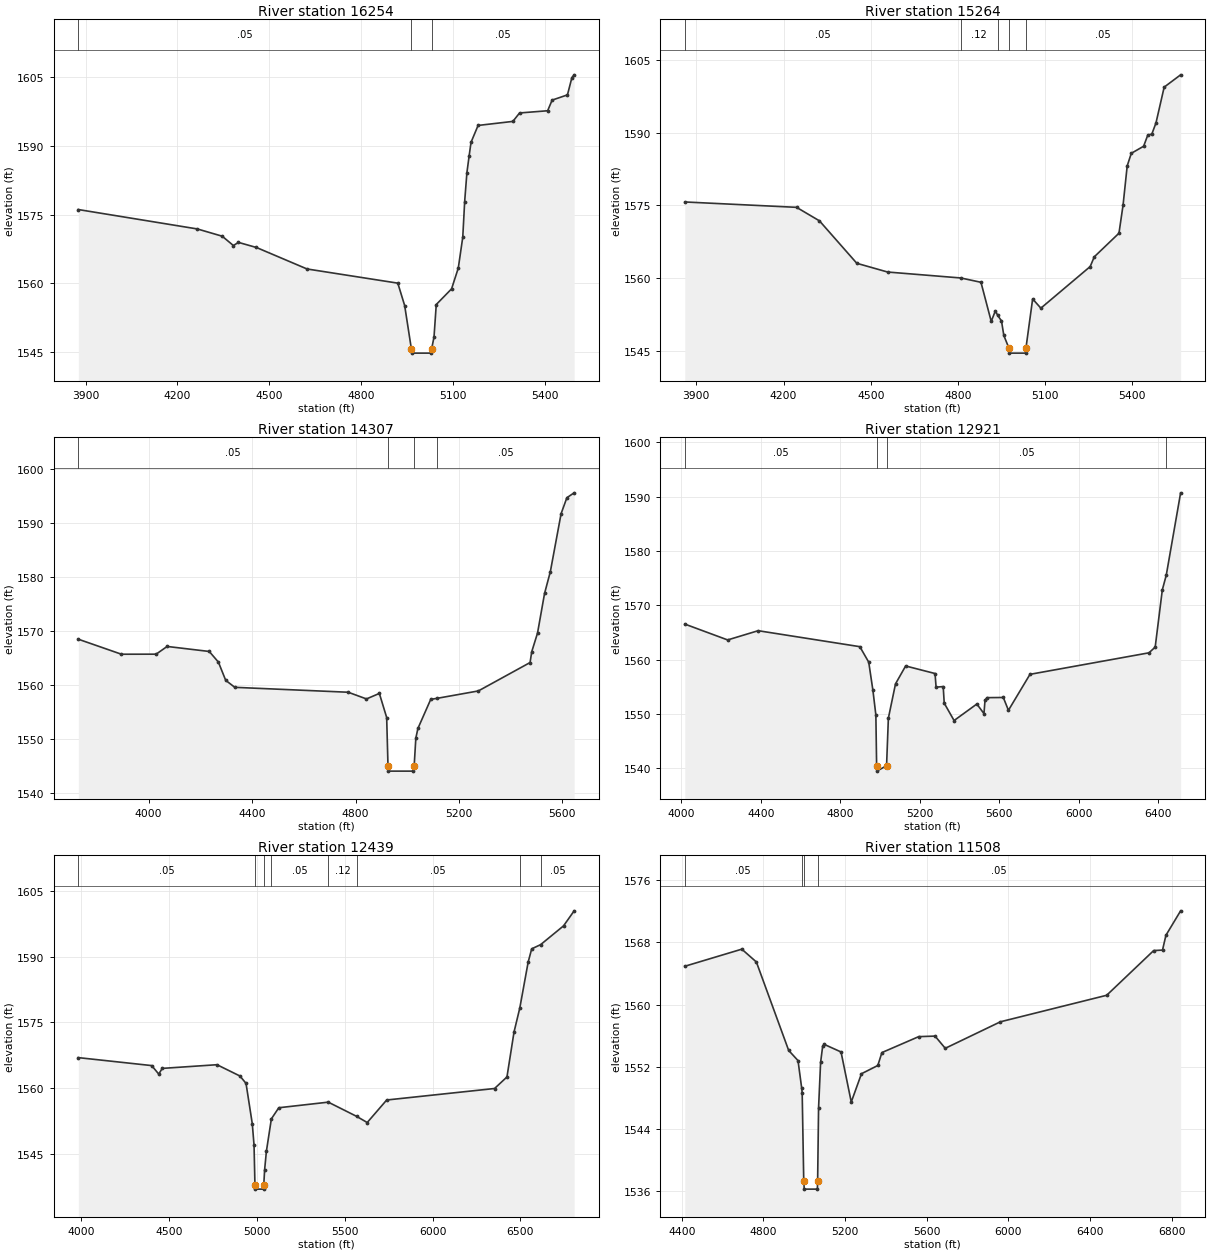
Type RM Length L Ch R = 1,16254,990,990,990
BEGIN DESCRIPTION:
Deadman Creek 15.0
END DESCRIPTION:
XS GIS Cut Line= 3
      1625855.01      6935838.03      1626355.00      6936838.00
      1626755.00      6937138.00
#Sta/Elev= 30
  3876.4 1576.10  4264.9 1571.87  4345.9 1570.29  4382.3 1568.26  4399.0 1568.94
  4457.7 1567.83  4622.7 1563.15  4918.9 1560.06  4941.3 1555.18  4963.0 1545.81
  4964.2 1544.81  5028.4 1544.81  5029.6 1545.81  5037.1 1548.33  5044.4 1555.40
  5094.4 1558.82  5116.3 1563.35  5130.9 1570.08  5137.1 1577.84  5144.4 1584.13
  5151.7 1587.80  5157.9 1590.76  5180.9 1594.43  5294.4 1595.31  5316.3 1597.15
  5407.9 1597.63  5422.5 1599.95  5472.5 1601.09  5487.1 1604.87  5494.4 1605.46
#Mann=3,-1,0
  3876.4    0.05       0  4963.0    0.07       0  5029.6    0.05       0
Bank Sta=4963,5029.6
Exp/Cntr=0.3,0.1

Type RM Length L Ch R = 1,15264,957,957,957
BEGIN DESCRIPTION:
Deadman Creek 14.0
END DESCRIPTION:
XS GIS Cut Line= 3
      1624905.03      6936538.03      1625605.00      6937438.00
      1626004.99      6937837.99
#Sta/Elev= 30
  3860.4 1575.72  4244.9 1574.61  4323.7 1571.82  4452.2 1563.06  4558.0 1561.26
  4810.2 1560.03  4879.3 1559.14  4914.6 1551.07  4929.0 1553.26  4936.9 1552.30
  4949.9 1551.17  4958.0 1548.16  4975.7 1545.52  4976.8 1544.52  5033.0 1544.52
  5034.0 1545.52  5057.1 1555.70  5085.4 1553.80  5255.1 1562.39  5269.2 1564.40
  5354.1 1569.27  5368.2 1575.08  5382.4 1583.16  5396.5 1585.76  5438.9 1587.22
  5453.1 1589.50  5467.2 1589.74  5481.4 1592.03  5509.6 1599.42  5566.2 1601.96
#Mann=5,-1,0
  3860.4    0.05       0  4810.2    0.12       0  4936.9    0.05       0
  4975.7    0.05       0  5034.0    0.05       0
Bank Sta=4975.7,5034
Exp/Cntr=0.3,0.1

Type RM Length L Ch R = 1,14307,1386,1386,1386
BEGIN DESCRIPTION:
Deadman Creek 13.0
END DESCRIPTION:
XS GIS Cut Line= 3
      1623977.69      6937059.73      1624855.00      6937988.00
      1625355.03      6938388.02
#Sta/Elev= 30
  3728.0 1568.44  3894.6 1565.66  4028.9 1565.67  4071.4 1567.10  4234.4 1566.17
  4269.6 1564.21  4297.9 1560.83  4333.1 1559.53  4771.6 1558.62  4842.4 1557.38
  4892.2 1558.40  4920.5 1553.94  4925.6 1545.01  4927.4 1544.01  5023.8 1544.01
  5025.6 1545.01  5026.9 1545.02  5033.3 1550.12  5041.3 1551.91  5090.9 1557.30
  5114.1 1557.48  5275.0 1558.86  5475.1 1564.12  5481.5 1566.12  5503.9 1569.57
  5531.1 1576.91  5553.5 1580.95  5595.1 1591.69  5617.5 1594.65  5645.6 1595.55
#Mann=4,-1,0
  3728.0    0.05       0  4925.6    0.03       0  5025.6    0.05       0
  5114.1    0.05       0
Bank Sta=4925.6,5025.6
Exp/Cntr=0.3,0.1

Type RM Length L Ch R = 1,12921,482,482,482
BEGIN DESCRIPTION:
Mapping XS e9edd131
END DESCRIPTION:
XS GIS Cut Line= 4
      1623399.56      6937247.21      1623571.44      6938054.52
      1623805.81      6938398.27      1625019.36      6938705.56
#Sta/Elev= 30
  4018.3 1566.53  4233.8 1563.61  4387.2 1565.31  4898.4 1562.37  4943.2 1559.52
  4964.2 1554.35  4979.1 1549.80  4982.9 1540.47  4983.8 1539.47  5032.9 1540.47
  5042.0 1549.21  5077.9 1555.53  5128.8 1558.82  5276.7 1557.43  5281.9 1554.92
  5317.7 1555.03  5322.9 1551.97  5372.4 1548.78  5486.9 1551.82  5522.7 1550.05
  5527.9 1552.48  5537.4 1552.99  5620.0 1553.02  5645.7 1550.66  5754.1 1557.28
  6352.4 1561.24  6383.7 1562.29  6419.6 1572.83  6439.4 1575.53  6511.6 1590.68
#Mann=4,-1,0
  4018.3    0.05       0  4982.9    0.05       0  5032.9    0.05       0
  6439.4    0.12       0
Bank Sta=4982.9,5032.9
Exp/Cntr=0.3,0.1

Type RM Length L Ch R = 1,12439,931,931,931
BEGIN DESCRIPTION:
Deadman Creek 12.0
END DESCRIPTION:
XS GIS Cut Line= 3
      1622449.40      6938678.15      1623455.00      6938588.00
      1625254.99      6938788.00
#Sta/Elev= 30
  3985.0 1566.94  4402.3 1565.12  4442.4 1563.18  4462.5 1564.48  4773.8 1565.32
  4904.3 1562.74  4939.0 1561.05  4974.6 1551.82  4984.6 1546.93  4989.7 1537.87
  4990.6 1536.87  5039.1 1536.87  5040.0 1537.87  5044.9 1541.34  5055.0 1545.57
  5083.2 1552.94  5125.4 1555.48  5406.9 1556.76  5567.6 1553.52  5628.5 1552.10
  5739.2 1557.25  6352.9 1559.88  6423.4 1562.52  6463.6 1572.79  6496.4 1578.28
  6544.1 1588.80  6564.2 1591.82  6615.0 1592.78  6745.3 1597.07  6805.7 1600.51
#Mann=8,-1,0
  3985.0    0.05       0  4989.7    0.05       0  5040.0    0.05       0
  5083.2    0.05       0  5406.9    0.12       0  5567.6    0.05       0
  6496.4    0.12       0  6615.0    0.05       0
Bank Sta=4989.7,5040
Exp/Cntr=0.3,0.1

Type RM Length L Ch R = 1,11508,974,974,974
BEGIN DESCRIPTION:
Deadman Creek 11.0
END DESCRIPTION:
XS GIS Cut Line= 3
      1622781.14      6939372.84      1623355.00      6939488.00
      1625196.83      6939398.61
#Sta/Elev= 30
  4415.1 1564.94  4694.4 1567.14  4765.8 1565.49  4924.0 1554.12  4969.8 1552.81
  4987.9 1549.25  4990.2 1548.69  4997.9 1537.28  4998.8 1537.28  5000.0 1536.28
  5064.7 1536.28  5065.9 1537.28  5070.5 1546.72  5080.5 1552.58  5090.5 1554.64
  5099.5 1554.88  5180.6 1553.92  5230.7 1547.48  5280.7 1551.12  5360.8 1552.18
  5380.8 1553.84  5561.1 1555.89  5641.2 1555.96  5691.2 1554.39  5961.5 1557.80
  6482.1 1561.21  6712.4 1566.96  6755.6 1567.02  6772.5 1568.93  6844.4 1572.07
#Mann=4,-1,0
  4415.1    0.05       0  4987.9    0.12       0  4998.8    0.07       0
  5065.9    0.05       0
Bank Sta=4998.8,5065.9
Exp/Cntr=0.3,0.1

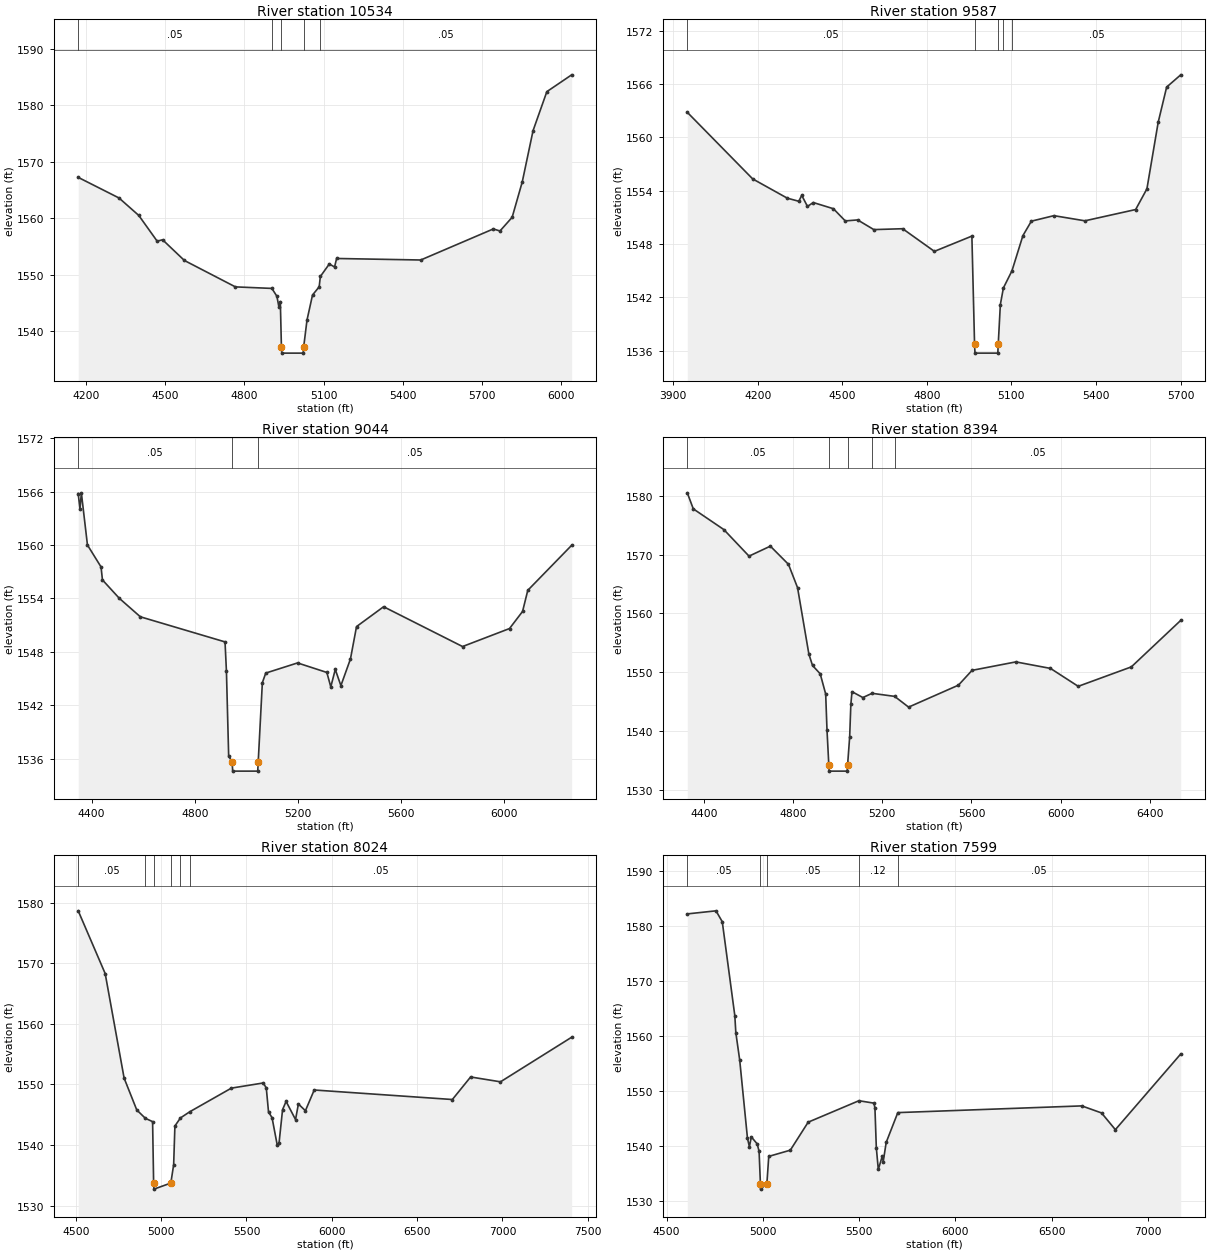
Type RM Length L Ch R = 1,10534,947,947,947
BEGIN DESCRIPTION:
Deadman Creek 10.0
END DESCRIPTION:
XS GIS Cut Line= 3
      1622804.98      6940137.99      1623605.00      6940338.00
      1624605.03      6940037.99
#Sta/Elev= 30
  4170.6 1567.24  4325.2 1563.59  4400.0 1560.50  4469.5 1555.95  4490.2 1556.19
  4572.6 1552.53  4765.9 1547.85  4904.0 1547.58  4923.1 1546.18  4930.8 1544.25
  4936.0 1545.25  4940.2 1537.12  4941.7 1536.12  5022.7 1536.12  5024.2 1537.12
  5037.0 1541.97  5057.9 1546.41  5083.1 1547.86  5087.6 1549.69  5121.4 1551.90
  5141.4 1551.38  5149.2 1552.88  5467.7 1552.61  5742.6 1558.11  5767.8 1557.75
  5813.9 1560.17  5852.2 1566.44  5893.1 1575.52  5945.3 1582.42  6039.3 1585.40
#Mann=5,-1,0
  4170.6    0.05       0  4904.0    0.12       0  4940.2    0.07       0
  5024.2    0.12       0  5087.6    0.05       0
Bank Sta=4940.2,5024.2
Exp/Cntr=0.3,0.1

Type RM Length L Ch R = 1,9587,543,543,543
BEGIN DESCRIPTION:
Deadman Creek 9.0
END DESCRIPTION:
XS GIS Cut Line= 3
      1622528.29      6941014.91      1623555.00      6941238.00
      1624255.03      6941238.00
#Sta/Elev= 30
  3950.0 1562.83  4182.0 1555.33  4304.8 1553.16  4345.7 1552.81  4356.0 1553.48
  4376.4 1552.23  4396.9 1552.67  4468.5 1551.97  4510.4 1550.60  4554.4 1550.71
  4611.8 1549.62  4714.1 1549.72  4826.7 1547.17  4959.7 1548.89  4969.2 1536.71
  4970.7 1535.71  5051.7 1535.71  5053.2 1536.71  5060.7 1541.18  5071.5 1543.05
  5101.9 1544.98  5140.7 1548.94  5170.7 1550.57  5250.7 1551.19  5360.7 1550.61
  5540.7 1551.88  5580.7 1554.21  5620.7 1561.71  5650.7 1565.67  5700.7 1567.05
#Mann=5,-1,0
  3950.0    0.05       0  4969.2    0.05       0  5053.2    0.05       0
  5071.5    0.12       0  5101.9    0.05       0
Bank Sta=4969.2,5053.2
Exp/Cntr=0.3,0.1

Type RM Length L Ch R = 1,9044,650,650,650
BEGIN DESCRIPTION:
Mapping XS 004d9b09
END DESCRIPTION:
XS GIS Cut Line= 3
      1622568.57      6941318.26      1623588.86      6941754.69
      1624383.24      6941632.74
#Sta/Elev= 30
  4347.8 1565.78  4354.6 1564.01  4360.0 1565.86  4383.6 1560.00  4436.3 1557.54
  4441.8 1556.08  4507.0 1554.02  4588.7 1551.94  4917.1 1549.12  4922.5 1545.85
  4931.2 1536.31  4944.9 1535.61  4946.7 1534.61  5043.9 1534.61  5045.7 1535.61
  5061.8 1544.54  5075.0 1545.62  5198.3 1546.76  5311.9 1545.69  5327.2 1544.07
  5344.6 1546.03  5366.3 1544.21  5403.4 1547.20  5427.0 1550.84  5532.0 1553.07
  5838.1 1548.60  6020.2 1550.62  6070.8 1552.54  6091.0 1554.91  6261.2 1559.97
#Mann=3,-1,0
  4347.8    0.05       0  4944.9    0.03       0  5045.7    0.05       0
Bank Sta=4944.9,5045.7
Exp/Cntr=0.3,0.1

Type RM Length L Ch R = 1,8394,370,370,370
BEGIN DESCRIPTION:
Mapping XS 288b7f23
END DESCRIPTION:
XS GIS Cut Line= 3
      1622258.50      6942171.76      1623541.93      6941942.83
      1624418.76      6941706.94
#Sta/Elev= 30
  4326.3 1580.52  4353.2 1577.79  4490.2 1574.26  4603.0 1569.74  4698.6 1571.44
  4779.9 1568.34  4820.5 1564.37  4871.3 1553.05  4887.6 1551.12  4922.1 1549.70
  4946.6 1546.26  4952.5 1540.11  4960.7 1534.13  4962.2 1533.13  5043.2 1533.13
  5044.7 1534.13  5054.1 1538.96  5059.4 1544.49  5064.5 1546.66  5113.2 1545.66
  5154.5 1546.38  5255.6 1545.86  5318.2 1544.03  5541.7 1547.77  5602.6 1550.29
  5798.9 1551.73  5954.2 1550.62  6078.5 1547.57  6316.6 1550.88  6538.0 1558.80
#Mann=5,-1,0
  4326.3    0.05       0  4960.7    0.05       0  5044.7    0.05       0
  5154.5     0.1       0  5255.6    0.05       0
Bank Sta=4960.7,5044.7
Exp/Cntr=0.3,0.1

Type RM Length L Ch R = 1,8024,425,425,425
BEGIN DESCRIPTION:
Mapping XS 3158f448
END DESCRIPTION:
XS GIS Cut Line= 3
      1622581.44      6942497.12      1623457.55      6942284.53
      1625390.09      6942759.56
#Sta/Elev= 30
  4513.9 1578.64  4671.9 1568.29  4782.9 1551.03  4857.1 1545.77  4907.8 1544.39
  4949.8 1543.85  4955.8 1533.71  4957.6 1532.71  5056.6 1533.71  5073.2 1536.74
  5080.5 1543.13  5113.0 1544.46  5168.3 1545.49  5411.5 1549.38  5598.2 1550.23
  5616.0 1549.41  5629.1 1545.44  5649.7 1544.51  5680.5 1539.93  5690.8 1540.33
  5711.4 1545.83  5732.0 1547.19  5787.4 1544.19  5804.1 1546.76  5845.3 1545.65
  5896.8 1549.07  6706.4 1547.50  6813.3 1551.22  6988.4 1550.42  7405.5 1557.78
#Mann=6,-1,0
  4513.9    0.05       0  4907.8    0.12       0  4955.8    0.07       0
  5056.6    0.12       0  5113.0    0.12       0  5168.3    0.05       0
Bank Sta=4955.8,5056.6
Exp/Cntr=0.3,0.1

Type RM Length L Ch R = 1,7599,537,537,537
BEGIN DESCRIPTION:
Deadman Creek 8.0
END DESCRIPTION:
XS GIS Cut Line= 3
      1622664.42      6942848.98      1623368.14      6942774.38
      1625175.91      6943185.53
#Sta/Elev= 30
  4607.8 1582.20  4756.8 1582.76  4789.4 1580.78  4854.5 1563.71  4859.8 1560.61
  4879.9 1555.63  4920.1 1541.46  4930.2 1539.86  4940.2 1541.67  4970.4 1540.40
  4980.5 1539.05  4987.4 1533.17  4988.0 1532.17  5021.0 1533.17  5030.7 1538.12
  5142.6 1539.25  5235.3 1544.34  5498.8 1548.24  5576.8 1547.80  5581.9 1546.93
  5589.1 1539.70  5599.4 1535.74  5619.8 1538.14  5625.0 1537.19  5640.4 1540.67
  5700.7 1546.08  6655.7 1547.30  6758.2 1546.02  6830.0 1542.98  7169.4 1556.74
#Mann=5,-1,0
  4607.8    0.05       0  4987.4    0.05       0  5021.0    0.05       0
  5498.8    0.12       0  5700.7    0.05       0
Bank Sta=4987.4,5021
Exp/Cntr=0.3,0.1

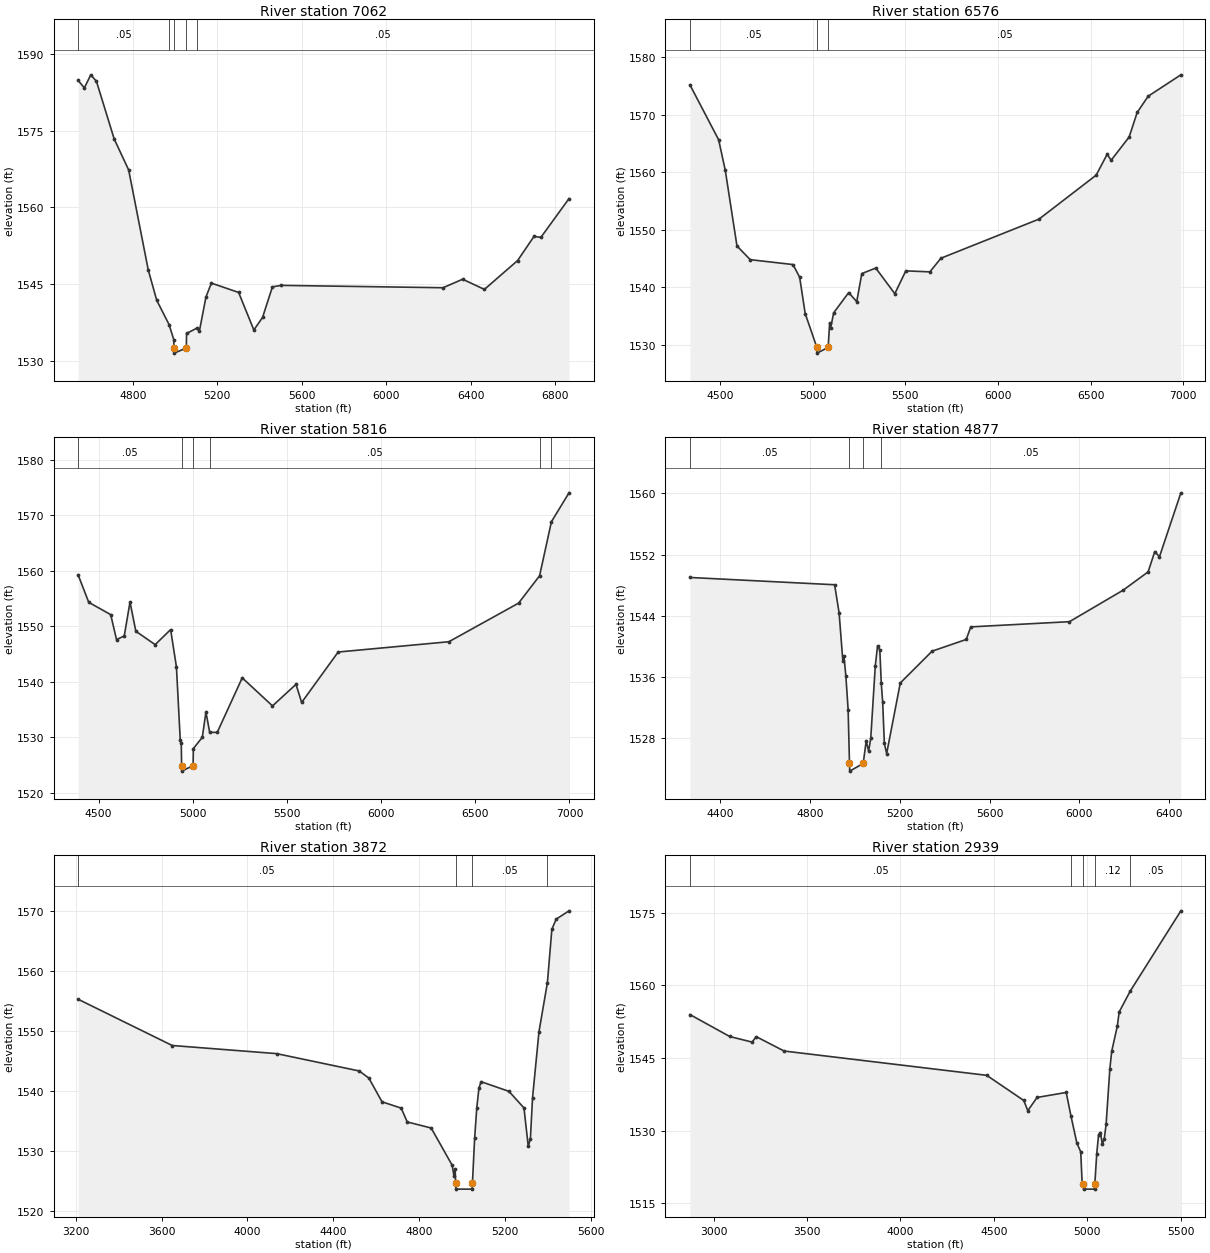
Type RM Length L Ch R = 1,7062,486,486,486
BEGIN DESCRIPTION:
Mapping XS 3e991679
END DESCRIPTION:
XS GIS Cut Line= 3
      1622755.42      6943231.48      1623296.50      6943302.34
      1625024.07      6943732.42
#Sta/Elev= 30
  4540.4 1584.81  4570.2 1583.36  4600.5 1585.91  4627.4 1584.64  4711.4 1573.37
  4780.1 1567.30  4872.8 1547.77  4913.1 1541.81  4971.4 1537.08  4993.8 1534.13
  4994.5 1532.49  4995.6 1531.49  5053.3 1532.49  5054.3 1535.34  5102.1 1536.35
  5115.5 1535.86  5146.4 1542.49  5171.9 1545.18  5301.0 1543.36  5373.1 1536.02
  5414.3 1538.46  5461.1 1544.44  5502.4 1544.74  6269.7 1544.28  6362.4 1545.94
  6465.5 1543.95  6622.8 1549.59  6700.3 1554.30  6733.4 1554.14  6866.4 1561.71
#Mann=5,-1,0
  4540.4    0.05       0  4971.4    0.12       0  4994.5    0.07       0
  5053.3    0.12       0  5102.1    0.05       0
Bank Sta=4994.5,5053.3
Exp/Cntr=0.3,0.1

Type RM Length L Ch R = 1,6576,760,760,760
BEGIN DESCRIPTION:
Deadman Creek 7.0
END DESCRIPTION:
XS GIS Cut Line= 3
      1622706.90      6943352.63      1623267.41      6943733.77
      1624986.38      6944697.89
#Sta/Elev= 30
  4337.7 1575.23  4492.5 1565.68  4528.4 1560.36  4591.4 1547.20  4663.2 1544.82
  4893.7 1543.97  4929.6 1541.77  4959.5 1535.45  5022.4 1529.56  5023.5 1528.56
  5083.4 1529.56  5091.5 1533.84  5097.2 1533.00  5113.2 1535.58  5194.2 1539.09
  5237.6 1537.52  5265.0 1542.40  5340.3 1543.36  5443.0 1538.90  5502.3 1542.87
  5632.4 1542.70  5691.7 1545.07  6221.2 1551.88  6529.3 1559.52  6588.6 1563.15
  6610.3 1562.12  6707.3 1566.16  6750.7 1570.43  6810.0 1573.26  6986.4 1576.98
#Mann=3,-1,0
  4337.7    0.05       0  5022.4    0.05       0  5083.4    0.05       0
Bank Sta=5022.4,5083.4
Exp/Cntr=0.3,0.1

Type RM Length L Ch R = 1,5816,939,939,939
BEGIN DESCRIPTION:
Deadman Creek 6.0
END DESCRIPTION:
XS GIS Cut Line= 3
      1622206.18      6944099.98      1622805.00      6944238.00
      1624664.95      6944951.96
#Sta/Elev= 30
  4391.1 1559.31  4447.7 1554.34  4564.4 1552.12  4595.1 1547.63  4636.2 1548.28
  4666.8 1554.39  4697.8 1549.13  4800.3 1546.72  4882.5 1549.43  4913.3 1542.72
  4933.7 1529.48  4938.9 1529.08  4940.9 1524.93  4941.9 1523.93  5001.8 1524.93
  5003.1 1527.99  5050.7 1530.02  5069.9 1534.58  5089.9 1530.92  5130.0 1530.91
  5262.7 1540.74  5423.4 1535.68  5548.2 1539.57  5578.2 1536.30  5772.2 1545.39
  6359.8 1547.24  6730.2 1554.20  6841.7 1559.13  6904.4 1568.86  6997.9 1574.07
#Mann=6,-1,0
  4391.1    0.05       0  4940.9    0.07       0  5001.8    0.05       0
  5089.9    0.05       0  6841.7    0.12       0  6904.4    0.05       0
Bank Sta=4940.9,5001.8
Exp/Cntr=0.3,0.1

Type RM Length L Ch R = 1,4877,1005,1005,1005
BEGIN DESCRIPTION:
Deadman Creek 5.0
END DESCRIPTION:
XS GIS Cut Line= 3
      1622071.62      6945108.92      1622818.99      6945146.29
      1624239.00      6945370.50
#Sta/Elev= 30
  4265.8 1549.02  4910.0 1548.07  4930.0 1544.39  4946.6 1538.12  4951.6 1538.73
  4960.0 1536.18  4970.1 1531.78  4976.2 1524.74  4977.3 1523.74  5037.2 1524.74
  5050.6 1527.68  5061.4 1526.36  5070.8 1528.00  5091.1 1537.50  5101.2 1540.09
  5111.3 1539.55  5117.7 1535.22  5123.9 1532.78  5131.5 1527.35  5141.7 1526.04
  5202.4 1535.25  5344.1 1539.40  5496.0 1540.93  5516.3 1542.57  5955.7 1543.25
  6194.6 1547.36  6305.9 1549.75  6335.3 1552.39  6356.5 1551.73  6451.7 1560.07
#Mann=4,-1,0
  4265.8    0.05       0  4976.2    0.05       0  5037.2    0.05       0
  5117.7    0.05       0
Bank Sta=4976.2,5037.2
Exp/Cntr=0.3,0.1

Type RM Length L Ch R = 1,3872,933,933,933
BEGIN DESCRIPTION:
Deadman Creek 4.0
END DESCRIPTION:
XS GIS Cut Line= 3
      1621554.98      6945237.99      1623155.00      6946038.00
      1623655.02      6946038.00
#Sta/Elev= 30
  3210.5 1555.25  3649.4 1547.55  4135.7 1546.20  4521.4 1543.31  4566.1 1542.13
  4627.6 1538.18  4717.1 1537.13  4745.0 1534.83  4856.8 1533.82  4954.7 1527.62
  4963.0 1525.86  4968.6 1526.92  4970.7 1524.65  4972.0 1523.65  5047.8 1523.65
  5049.1 1524.65  5059.4 1532.12  5069.4 1537.19  5079.4 1540.43  5089.4 1541.53
  5219.4 1539.92  5289.4 1537.16  5309.4 1530.77  5319.4 1532.06  5329.4 1538.88
  5359.4 1549.85  5398.7 1558.02  5419.4 1566.88  5439.4 1568.57  5499.4 1569.96
#Mann=4,-1,0
  3210.5    0.05       0  4970.7    0.05       0  5049.1    0.05       0
  5398.7    0.05       0
Bank Sta=4970.7,5049.1
Exp/Cntr=0.3,0.1

Type RM Length L Ch R = 1,2939,961,961,961
BEGIN DESCRIPTION:
Deadman Creek 3.0
END DESCRIPTION:
XS GIS Cut Line= 3
      1621505.01      6945488.01      1623105.00      6946888.00
      1623604.99      6946888.00
#Sta/Elev= 30
  2873.9 1553.98  3086.5 1549.45  3206.6 1548.29  3228.4 1549.42  3377.4 1546.45
  4461.3 1541.43  4659.7 1536.23  4681.0 1534.13  4730.8 1536.86  4886.5 1537.89
  4912.0 1533.03  4943.4 1527.46  4964.3 1525.62  4971.9 1518.94  4978.4 1518.92
  4979.4 1517.92  5038.4 1517.92  5039.5 1518.92  5049.9 1525.26  5059.9 1529.19
  5069.9 1529.61  5079.9 1527.19  5089.9 1528.24  5099.9 1531.29  5119.9 1542.69
  5129.9 1546.39  5159.9 1551.58  5169.9 1554.52  5229.2 1558.84  5499.9 1575.41
#Mann=5,-1,0
  2873.9    0.05       0  4912.0    0.12       0  4978.4    0.07       0
  5039.5    0.12       0  5229.2    0.05       0
Bank Sta=4978.4,5039.5
Exp/Cntr=0.3,0.1

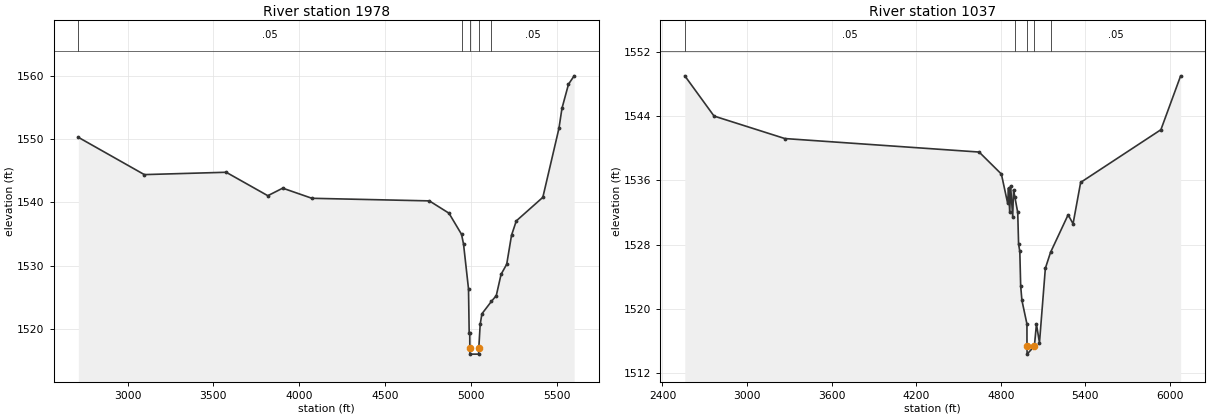
Type RM Length L Ch R = 1,1978,941,941,941
BEGIN DESCRIPTION:
Deadman Creek 2.0
END DESCRIPTION:
XS GIS Cut Line= 3
      1620955.03      6946338.02      1622755.00      6947738.00
      1623355.01      6947638.00
#Sta/Elev= 30
  2713.2 1550.25  3097.7 1544.36  3574.6 1544.73  3817.1 1541.03  3904.0 1542.22
  4074.1 1540.62  4758.2 1540.21  4872.3 1538.27  4945.7 1534.93  4957.3 1533.39
  4986.3 1526.32  4990.3 1519.32  4993.5 1519.32  4994.0 1517.01  4994.9 1516.01
  5045.5 1516.01  5046.4 1517.01  5054.3 1520.71  5064.5 1522.38  5119.8 1524.34
  5148.1 1525.25  5176.0 1528.61  5208.9 1530.21  5236.8 1534.77  5264.7 1537.05
  5419.3 1540.77  5513.1 1551.65  5530.8 1554.83  5568.8 1558.63  5601.8 1559.96
#Mann=5,-1,0
  2713.2    0.05       0  4945.7    0.12       0  4994.0    0.07       0
  5046.4    0.12       0  5119.8    0.05       0
Bank Sta=4994,5046.4
Exp/Cntr=0.3,0.1

Type RM Length L Ch R = 1,1037,0,0,0
BEGIN DESCRIPTION:
Deadman Creek 1.0
END DESCRIPTION:
XS GIS Cut Line= 3
      1620955.00      6946538.00      1622355.00      6948538.00
      1623354.95      6948138.02
#Sta/Elev= 30
  2558.5 1549.02  2766.0 1544.01  3268.7 1541.21  4647.1 1539.53  4804.9 1536.79
  4849.4 1533.16  4855.5 1535.05  4864.2 1532.01  4870.3 1535.32  4885.2 1531.48
  4891.3 1534.84  4900.9 1533.89  4920.9 1532.01  4927.0 1528.06  4935.7 1527.15
  4941.8 1522.87  4950.6 1521.07  4986.3 1518.12  4986.6 1515.37  4987.5 1514.37
  5039.1 1515.37  5053.7 1518.10  5075.2 1515.79  5116.9 1525.05  5153.5 1527.03
  5278.5 1531.72  5313.5 1530.60  5367.4 1535.75  5936.8 1542.31  6076.8 1549.01
#Mann=5,-1,0
  2558.5    0.05       0  4900.9    0.12       0  4986.6    0.07       0
  5039.1    0.12       0  5153.5    0.05       0
Bank Sta=4986.6,5039.1
Exp/Cntr=0.3,0.1

Chan Stop Cuts=-1