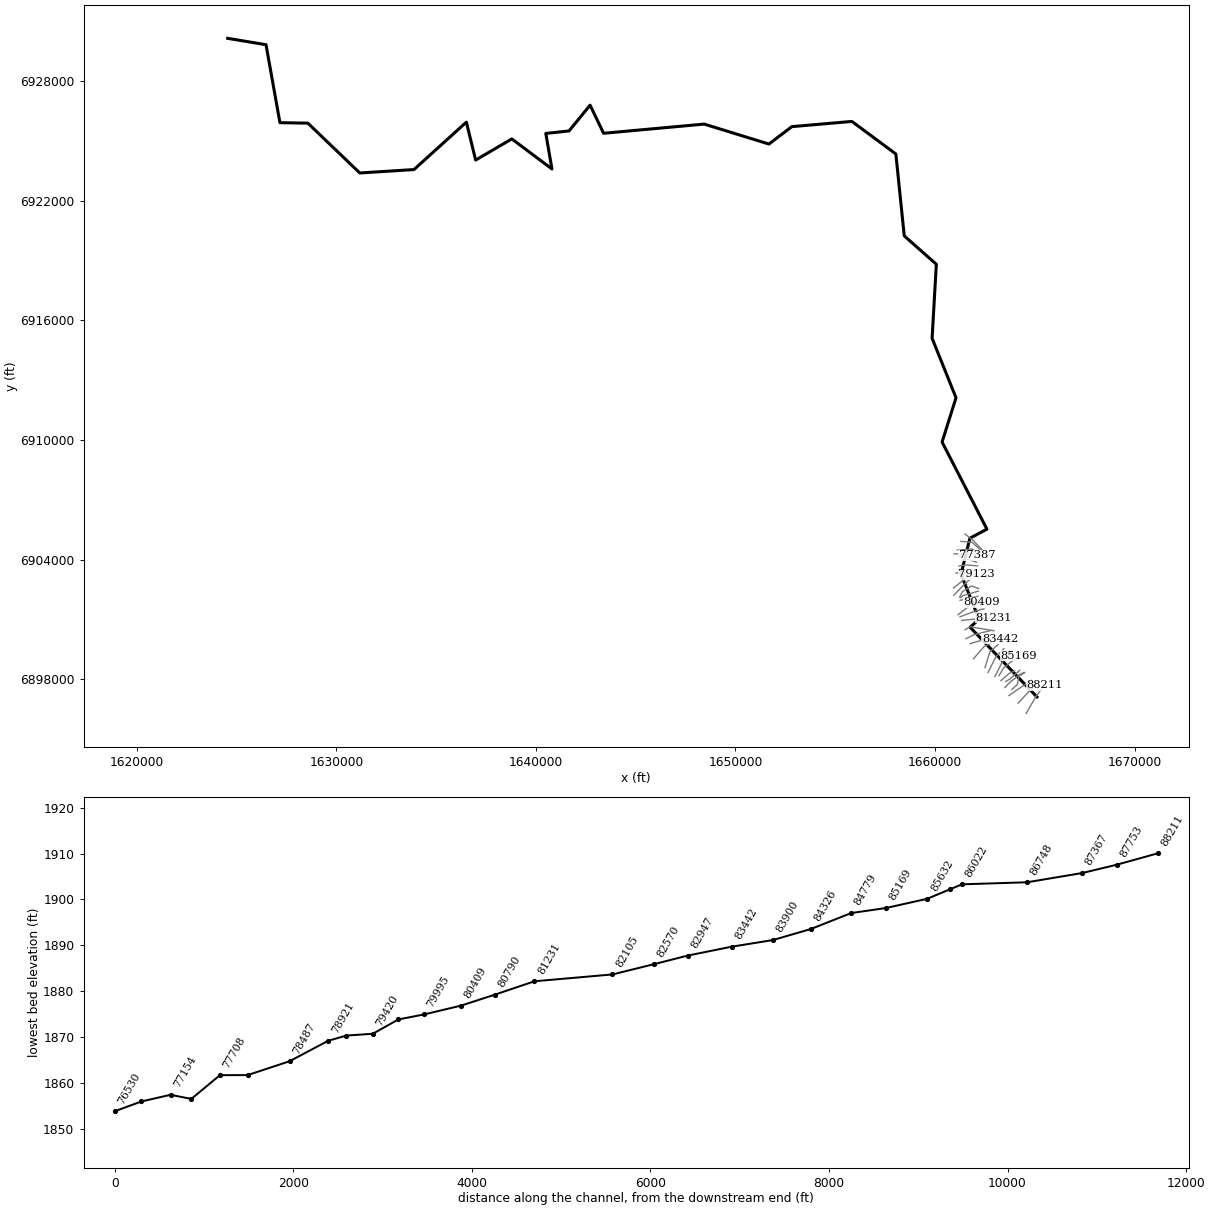
--- Long Creek.prj (project) ---

Proj Title=Long Creek Base Level Engineering
Current Plan=p01
Default Exp/Contr=0.3,0.1
English Units
Geom File=g01
Flow File=f01
Plan File=p01
BEGIN DESCRIPTION:
Long Creek
END DESCRIPTION:

--- Long Creek.p01 (plan) ---

Plan Title=Multiple Run
Short Identifier=Multiple
Geom File=g01
Flow File=f01
Subcritical Flow
K Sum by GR= 0
Std Step Tol= 0.01
Critical Tol= 0.01
Num of Std Step Trials= 20
Max Error Tol= 0.3
Flow Tol Ratio= 0.001
Split Flow NTrial= 30
Split Flow Tol= 0.02
Split Flow Ratio= 0.02
Log Output Level= 0
Friction Slope Method= 1
Unsteady Friction Slope Method= 2
Unsteady Bridges Friction Slope Method= 1
Parabolic Critical Depth
Global Vel Dist=  1 , 1 , 1
Global Log Level= 0
CheckData=True
Encroach Param= -1, 0, 0, 0
BEGIN DESCRIPTION:
Multiple Run
END DESCRIPTION:

--- Long Creek.f01 (steady flow) ---

Flow Title=Multiple
Number of Profiles=7
Profile Names=10-year,25-year,50-year,1pct_min,100-year,1pct_plu,500-year
River Rch & RM= Long Creek,Reach-1,88211
     307     428     529     325     649    1294     988
River Rch & RM= Long Creek,Reach-1,87753
     396     558     693     428     853    1703    1312
River Rch & RM= Long Creek,Reach-1,78017
     450     637     794     493     983    1961    1524
River Rch & RM= Long Creek,Reach-1,72880
     829    1207    1534     968    1930    3852    3098
River Rch & RM= Long Creek,Reach-1,66577
    1080    1589    2033    1290    2574    5137    4183
River Rch & RM= Long Creek,Reach-1,61899
    1109    1631    2088    1324    2642    5272    4291
River Rch & RM= Long Creek,Reach-1,59311
    1425    2115    2722    1736    3463    6910    5683
River Rch & RM= Long Creek,Reach-1,52281
    1576    2345    3024    1931    3854    7689    6343
River Rch & RM= Long Creek,Reach-1,47286
    1707    2547    3292    2107    4203    8386    6944
River Rch & RM= Long Creek,Reach-1,42871
    1731    2582    3335    2133    4256    8492    7024
River Rch & RM= Long Creek,Reach-1,37772
    1767    2634    3403    2176    4341    8662    7162
River Rch & RM= Long Creek,Reach-1,33467
    1785    2661    3436    2196    4382    8743    7223
River Rch & RM= Long Creek,Reach-1,30827
    1838    2743    3544    2267    4524    9026    7468
River Rch & RM= Long Creek,Reach-1,26018
    2103    3154    4091    2626    5239   10453    8706
River Rch & RM= Long Creek,Reach-1,18182
    2106    3157    4092    2625    5237   10450    8694
River Rch & RM= Long Creek,Reach-1,14549
    3039    4605    6015    3886    7753   15470   13048
River Rch & RM= Long Creek,Reach-1,8815
    3061    4636    6055    3910    7802   15567   13123
Boundary for River Rch & Prof#=Long Creek,Reach-1,1
Up Type=0
Dn Type=3
Dn Slope=0.001
Boundary for River Rch & Prof#=Long Creek,Reach-1,2
Up Type=0
Dn Type=3
Dn Slope=0.001
Boundary for River Rch & Prof#=Long Creek,Reach-1,3
Up Type=0
Dn Type=3
Dn Slope=0.001
Boundary for River Rch & Prof#=Long Creek,Reach-1,4
Up Type=0
Dn Type=3
Dn Slope=0.001
Boundary for River Rch & Prof#=Long Creek,Reach-1,5
Up Type=0
Dn Type=3
Dn Slope=0.001
Boundary for River Rch & Prof#=Long Creek,Reach-1,6
Up Type=0
Dn Type=3
Dn Slope=0.001
Boundary for River Rch & Prof#=Long Creek,Reach-1,7
Up Type=0
Dn Type=3
Dn Slope=0.001

--- Long Creek.g01 (geometry) ---

Geom Title=Existing Conditions

River Reach=Long Creek,Reach-1
Reach XY= 30
      1665113.49      6897118.47      1661761.60      6900612.57
      1662208.29      6901013.89      1661306.04      6903277.56
      1661750.26      6905075.07      1662603.43      6905531.91
      1660356.08      6909898.54      1661055.48      6912117.84
      1659856.20      6915098.50      1660068.21      6918810.68
      1658460.71      6920235.65      1658039.79      6924341.04
      1655835.15      6925972.50      1652826.40      6925710.80
      1651680.08      6924837.80      1648434.94      6925838.22
      1643393.36      6925378.37      1642715.70      6926787.30
      1641661.19      6925495.81      1640496.88      6925369.64
      1640805.00      6923588.00      1638793.89      6925095.70
      1636980.97      6924034.82      1636515.50      6925936.78
      1633891.68      6923559.34      1631175.03      6923388.07
      1628571.57      6925886.13      1627173.06      6925908.81
      1626475.21      6929818.41      1624555.00      6930138.00

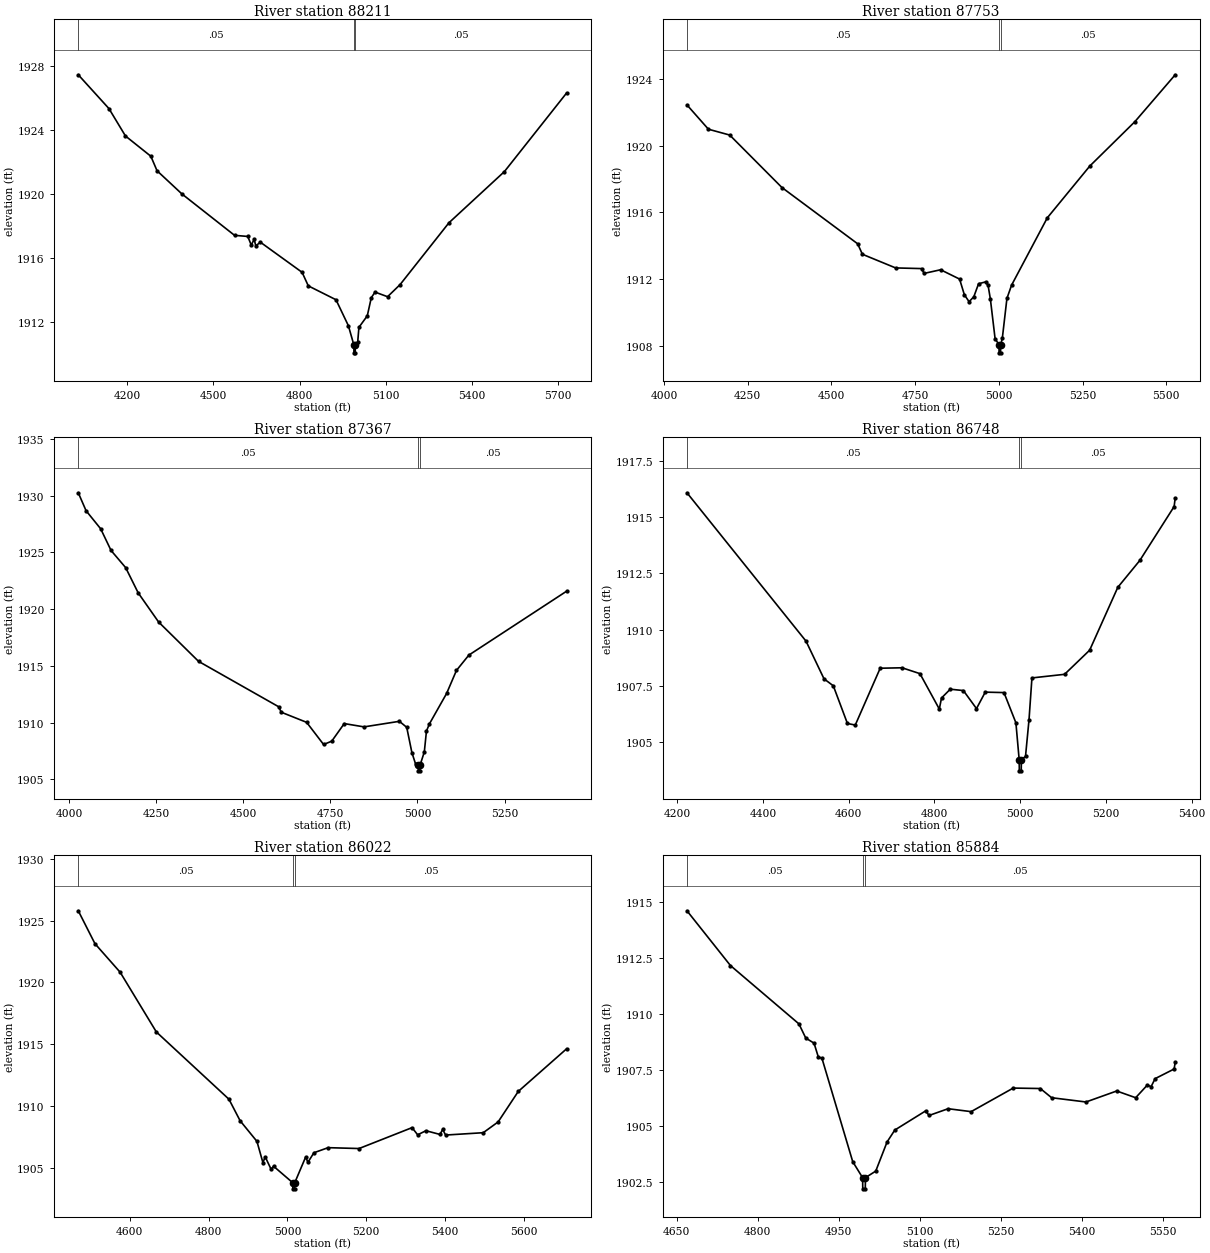
Type RM Length L Ch R = 1,88211,458,458,458
BEGIN DESCRIPTION:
Long Creek 149.0
END DESCRIPTION:
XS GIS Cut Line= 3
      1664573.49      6896295.18      1665055.00      6897138.00
      1665498.70      6897718.35
#Sta/Elev= 30
  4029.1 1927.48  4136.0 1925.36  4193.6 1923.64  4282.0 1922.37  4303.6 1921.46
  4390.0 1920.01  4573.6 1917.41  4619.7 1917.34  4631.9 1916.80  4642.0 1917.16
  4647.7 1916.75  4663.6 1916.98  4809.0 1915.09  4830.6 1914.24  4927.1 1913.37
  4970.3 1911.74  4989.3 1910.54  4989.7 1910.04  4994.0 1910.04  4994.4 1910.54
  5002.9 1910.75  5007.0 1911.64  5036.1 1912.36  5050.1 1913.50  5063.2 1913.85
  5106.8 1913.56  5150.4 1914.32  5320.8 1918.20  5514.0 1921.41  5730.3 1926.33
#Mann=3,-1,0
  4029.1    0.05       0  4989.3    0.03       0  4994.4    0.05       0
Bank Sta=4989.3,4994.4
Exp/Cntr=0.3,0.1

Type RM Length L Ch R = 1,87753,386,386,386
BEGIN DESCRIPTION:
Mapping XS 3d30dd6b
END DESCRIPTION:
XS GIS Cut Line= 2
      1664166.28      6896806.09      1665155.93      6897877.18
#Sta/Elev= 30
  4068.3 1922.46  4132.4 1921.00  4196.0 1920.65  4351.9 1917.50  4578.1 1914.12
  4592.3 1913.49  4691.5 1912.67  4769.2 1912.63  4776.6 1912.34  4825.9 1912.56
  4882.6 1912.00  4896.8 1911.06  4911.0 1910.64  4925.1 1910.94  4939.3 1911.72
  4960.3 1911.83  4967.7 1911.62  4974.5 1910.81  4988.7 1908.41  5000.2 1908.07
  5000.6 1907.57  5005.0 1907.57  5005.4 1908.07  5010.2 1908.44  5024.0 1910.84
  5038.0 1911.64  5144.6 1915.68  5271.6 1918.79  5406.0 1921.45  5526.6 1924.27
#Mann=3,-1,0
  4068.3    0.05       0  5000.2    0.05       0  5005.4    0.05       0
Bank Sta=5000.2,5005.4
Exp/Cntr=0.3,0.1

Type RM Length L Ch R = 1,87367,619,619,619
BEGIN DESCRIPTION:
Long Creek 148.0
END DESCRIPTION:
XS GIS Cut Line= 3
      1663704.97      6897187.98      1664505.00      6897738.00
      1664855.02      6897988.01
#Sta/Elev= 30
  4026.8 1930.24  4049.2 1928.66  4091.1 1927.07  4120.9 1925.16  4162.8 1923.65
  4198.7 1921.43  4257.4 1918.86  4371.9 1915.40  4601.9 1911.40  4609.3 1910.92
  4682.1 1910.03  4730.7 1908.08  4754.1 1908.37  4790.0 1909.92  4846.8 1909.63
  4948.3 1910.12  4969.3 1909.59  4984.1 1907.37  4994.6 1906.37  5002.4 1906.26
  5002.8 1905.76  5007.2 1905.76  5007.6 1906.26  5019.8 1907.43  5025.9 1909.26
  5034.5 1909.90  5083.7 1912.57  5112.0 1914.60  5147.6 1915.95  5427.8 1921.57
#Mann=3,-1,0
  4026.8    0.05       0  5002.4    0.03       0  5007.6    0.05       0
Bank Sta=5002.4,5007.6
Exp/Cntr=0.3,0.1

Type RM Length L Ch R = 1,86748,726,726,726
BEGIN DESCRIPTION:
Mapping XS ea828212
END DESCRIPTION:
XS GIS Cut Line= 4
      1663849.03      6897492.13      1664126.83      6897743.88
      1664213.98      6898166.20      1664500.14      6898335.47
#Sta/Elev= 30
  4222.9 1916.07  4500.6 1909.49  4542.5 1907.82  4564.2 1907.51  4597.1 1905.84
  4615.4 1905.77  4673.5 1908.29  4724.5 1908.31  4766.2 1908.05  4811.4 1906.48
  4816.5 1906.97  4836.9 1907.36  4867.5 1907.30  4898.1 1906.50  4918.5 1907.23
  4962.2 1907.21  4990.0 1905.87  4997.6 1904.24  4998.0 1903.74  5002.4 1903.74
  5002.8 1904.24  5012.4 1904.38  5020.6 1906.01  5027.4 1907.86  5103.5 1908.02
  5162.0 1909.09  5227.7 1911.88  5279.0 1913.07  5359.0 1915.46  5361.5 1915.84
#Mann=3,-1,0
  4222.9    0.05       0  4997.6    0.03       0  5002.8    0.05       0
Bank Sta=4997.6,5002.8
Exp/Cntr=0.3,0.1

Type RM Length L Ch R = 1,86022,138,138,138
BEGIN DESCRIPTION:
Long Creek 147.0
END DESCRIPTION:
XS GIS Cut Line= 5
      1663504.98      6897587.98      1663802.82      6897901.84
      1663998.18      6898030.78      1664205.72      6898223.55
      1664465.07      6898349.20
#Sta/Elev= 30
  4469.7 1925.79  4512.0 1923.13  4575.9 1920.82  4667.7 1915.99  4851.8 1910.55
  4880.1 1908.81  4922.8 1907.14  4937.9 1905.43  4943.9 1905.88  4958.9 1904.87
  4964.9 1905.13  5013.4 1903.80  5013.9 1903.30  5018.4 1903.30  5018.8 1903.80
  5046.3 1905.87  5052.2 1905.45  5067.3 1906.22  5103.4 1906.63  5181.8 1906.56
  5316.2 1908.25  5330.4 1907.67  5351.4 1908.00  5387.1 1907.70  5393.9 1908.11
  5401.2 1907.65  5496.7 1907.84  5534.4 1908.71  5585.6 1911.18  5707.9 1914.62
#Mann=3,-1,0
  4469.7    0.05       0  5013.4    0.03       0  5018.8    0.05       0
Bank Sta=5013.4,5018.8
Exp/Cntr=0.3,0.1

Type RM Length L Ch R = 1,85884,252,252,252
BEGIN DESCRIPTION:
Mapping XS 210f85c6
END DESCRIPTION:
XS GIS Cut Line= 3
      1663545.22      6897895.79      1663749.23      6898012.98
      1664251.35      6898454.50
#Sta/Elev= 30
  4668.8 1914.59  4749.3 1912.15  4876.1 1909.55  4888.7 1908.92  4904.1 1908.69
  4911.8 1908.09  4918.8 1908.01  4975.7 1903.41  4993.9 1902.70  4994.3 1902.20
  4998.9 1902.20  4999.3 1902.70  5018.3 1902.99  5039.3 1904.29  5053.6 1904.82
  5110.5 1905.67  5117.1 1905.47  5152.3 1905.77  5194.9 1905.64  5272.8 1906.69
  5323.0 1906.67  5343.9 1906.26  5407.5 1906.07  5464.4 1906.56  5499.5 1906.26
  5521.3 1906.83  5528.0 1906.75  5535.5 1907.11  5570.7 1907.54  5572.7 1907.84
#Mann=3,-1,0
  4668.8    0.05       0  4993.9    0.03       0  4999.3    0.05       0
Bank Sta=4993.9,4999.3
Exp/Cntr=0.3,0.1

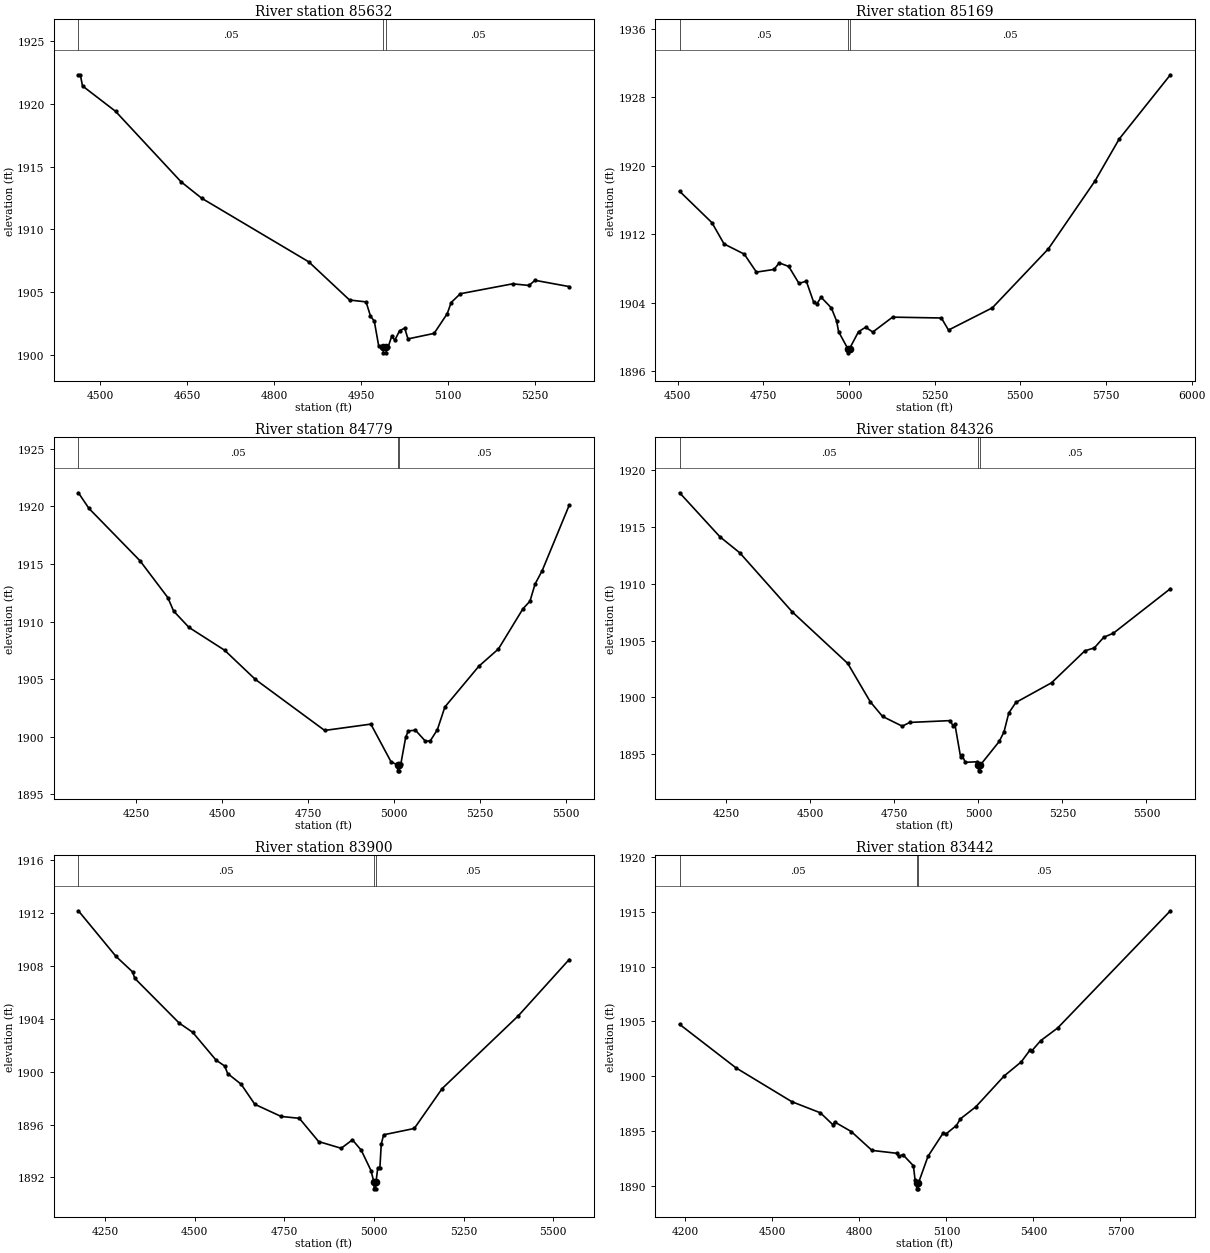
Type RM Length L Ch R = 1,85632,463,463,463
BEGIN DESCRIPTION:
Long Creek 146.0
END DESCRIPTION:
XS GIS Cut Line= 3
      1663305.04      6897938.03      1663705.00      6898288.00
      1663987.98      6898425.32
#Sta/Elev= 30
  4462.8 1922.31  4466.1 1922.31  4469.9 1921.42  4526.8 1919.40  4639.8 1913.78
  4675.4 1912.47  4860.0 1907.40  4930.2 1904.36  4958.7 1904.21  4966.3 1903.08
  4972.9 1902.67  4980.5 1900.69  4988.2 1900.65  4988.6 1900.15  4993.2 1900.15
  4993.6 1900.65  4997.0 1900.65  5002.8 1901.46  5008.3 1901.16  5016.5 1901.91
  5025.3 1902.12  5030.9 1901.26  5076.0 1901.70  5098.6 1903.27  5105.4 1904.16
  5121.2 1904.86  5211.4 1905.65  5239.6 1905.52  5249.9 1905.93  5308.8 1905.43
#Mann=3,-1,0
  4462.8    0.05       0  4988.2    0.03       0  4993.6    0.05       0
Bank Sta=4988.2,4993.6
Exp/Cntr=0.3,0.1

Type RM Length L Ch R = 1,85169,390,390,390
BEGIN DESCRIPTION:
Long Creek 145.0
END DESCRIPTION:
XS GIS Cut Line= 3
      1663204.99      6898187.99      1663455.00      6898588.00
      1664205.01      6899188.01
#Sta/Elev= 30
  4505.7 1917.00  4600.1 1913.33  4635.4 1910.85  4694.4 1909.66  4729.8 1907.56
  4781.1 1907.87  4796.4 1908.64  4824.1 1908.22  4854.2 1906.23  4875.4 1906.51
  4896.6 1904.08  4906.1 1903.83  4918.5 1904.63  4948.5 1903.38  4963.9 1901.84
  4969.7 1900.60  4996.3 1898.63  4996.7 1898.13  5001.8 1898.63  5027.8 1900.60
  5048.6 1901.12  5069.5 1900.56  5127.1 1902.30  5269.6 1902.20  5290.4 1900.79
  5418.4 1903.39  5581.7 1910.27  5717.8 1918.20  5788.2 1923.09  5937.9 1930.61
#Mann=3,-1,0
  4505.7    0.05       0  4996.3    0.03       0  5001.8    0.05       0
Bank Sta=4996.3,5001.8
Exp/Cntr=0.3,0.1

Type RM Length L Ch R = 1,84779,453,453,453
BEGIN DESCRIPTION:
Long Creek 144.0
END DESCRIPTION:
XS GIS Cut Line= 3
      1663005.02      6898138.04      1663405.00      6898938.00
      1663805.00      6899288.00
#Sta/Elev= 30
  4082.4 1921.19  4113.1 1919.83  4261.2 1915.29  4342.3 1912.08  4359.1 1910.91
  4403.8 1909.49  4507.2 1907.51  4596.7 1904.97  4797.9 1900.54  4932.1 1901.09
  4990.5 1897.83  5009.6 1897.53  5010.1 1897.03  5014.7 1897.03  5015.1 1897.53
  5019.0 1897.59  5033.3 1899.94  5040.9 1900.50  5061.7 1900.56  5090.2 1899.62
  5104.4 1899.62  5125.3 1900.60  5147.2 1902.58  5245.9 1906.12  5302.8 1907.62
  5374.0 1911.11  5394.4 1911.77  5409.1 1913.25  5430.0 1914.43  5508.3 1920.10
#Mann=3,-1,0
  4082.4    0.05       0  5009.6    0.05       0  5015.1    0.05       0
Bank Sta=5009.6,5015.1
Exp/Cntr=0.3,0.1

Type RM Length L Ch R = 1,84326,426,426,426
BEGIN DESCRIPTION:
Long Creek 143.0
END DESCRIPTION:
XS GIS Cut Line= 3
      1662654.99      6898337.99      1663055.00      6899138.00
      1663454.98      6899537.98
#Sta/Elev= 30
  4111.1 1918.01  4231.3 1914.13  4290.0 1912.73  4446.5 1907.52  4611.4 1902.99
  4678.5 1899.61  4714.8 1898.33  4773.5 1897.47  4795.9 1897.80  4916.1 1897.96
  4924.5 1897.50  4930.1 1897.64  4946.8 1894.80  4952.4 1894.89  4960.8 1894.29
  4997.2 1894.34  4999.9 1894.04  5000.4 1893.54  5005.1 1893.54  5005.5 1894.04
  5062.1 1896.13  5076.2 1896.97  5090.4 1898.63  5111.6 1899.56  5217.7 1901.29
  5316.7 1904.10  5344.9 1904.36  5373.2 1905.30  5401.5 1905.65  5571.2 1909.57
#Mann=3,-1,0
  4111.1    0.05       0  4999.9    0.03       0  5005.5    0.05       0
Bank Sta=4999.9,5005.5
Exp/Cntr=0.3,0.1

Type RM Length L Ch R = 1,83900,458,458,458
BEGIN DESCRIPTION:
Long Creek 142.0
END DESCRIPTION:
XS GIS Cut Line= 3
      1662504.99      6898587.98      1662755.00      6899388.00
      1663155.02      6899738.01
#Sta/Elev= 30
  4175.0 1912.18  4279.8 1908.73  4326.4 1907.55  4332.2 1907.07  4456.3 1903.68
  4494.0 1902.98  4559.0 1900.88  4583.6 1900.42  4591.5 1899.86  4629.2 1899.05
  4667.4 1897.53  4740.8 1896.61  4791.6 1896.47  4845.5 1894.71  4908.4 1894.20
  4939.8 1894.84  4964.5 1894.05  4991.7 1892.51  4999.8 1891.63  5000.3 1891.13
  5005.1 1891.13  5005.5 1891.63  5010.6 1892.73  5016.5 1892.73  5020.3 1894.52
  5026.9 1895.22  5112.4 1895.70  5190.2 1898.72  5402.8 1904.23  5544.7 1908.49
#Mann=3,-1,0
  4175.0    0.05       0  4999.8    0.03       0  5005.5    0.05       0
Bank Sta=4999.8,5005.5
Exp/Cntr=0.3,0.1

Type RM Length L Ch R = 1,83442,495,495,495
BEGIN DESCRIPTION:
Long Creek 141.0
END DESCRIPTION:
XS GIS Cut Line= 3
      1661934.95      6899033.14      1662455.00      6899638.00
      1663254.98      6900037.99
#Sta/Elev= 30
  4180.2 1904.72  4374.9 1900.74  4566.9 1897.66  4665.7 1896.64  4708.5 1895.56
  4715.1 1895.80  4772.1 1894.93  4843.5 1893.21  4928.0 1892.95  4935.6 1892.67
  4949.9 1892.82  4986.3 1891.81  4991.9 1890.54  4997.4 1890.20  4997.9 1889.70
  5002.7 1889.70  5003.2 1890.20  5036.6 1892.67  5089.7 1894.83  5098.1 1894.70
  5134.4 1895.48  5148.4 1896.09  5201.5 1897.19  5299.3 1900.01  5358.0 1901.29
  5388.8 1902.39  5394.4 1902.30  5425.1 1903.23  5483.8 1904.39  5872.3 1915.09
#Mann=3,-1,0
  4180.2    0.05       0  4997.4    0.03       0  5003.2    0.05       0
Bank Sta=4997.4,5003.2
Exp/Cntr=0.3,0.1

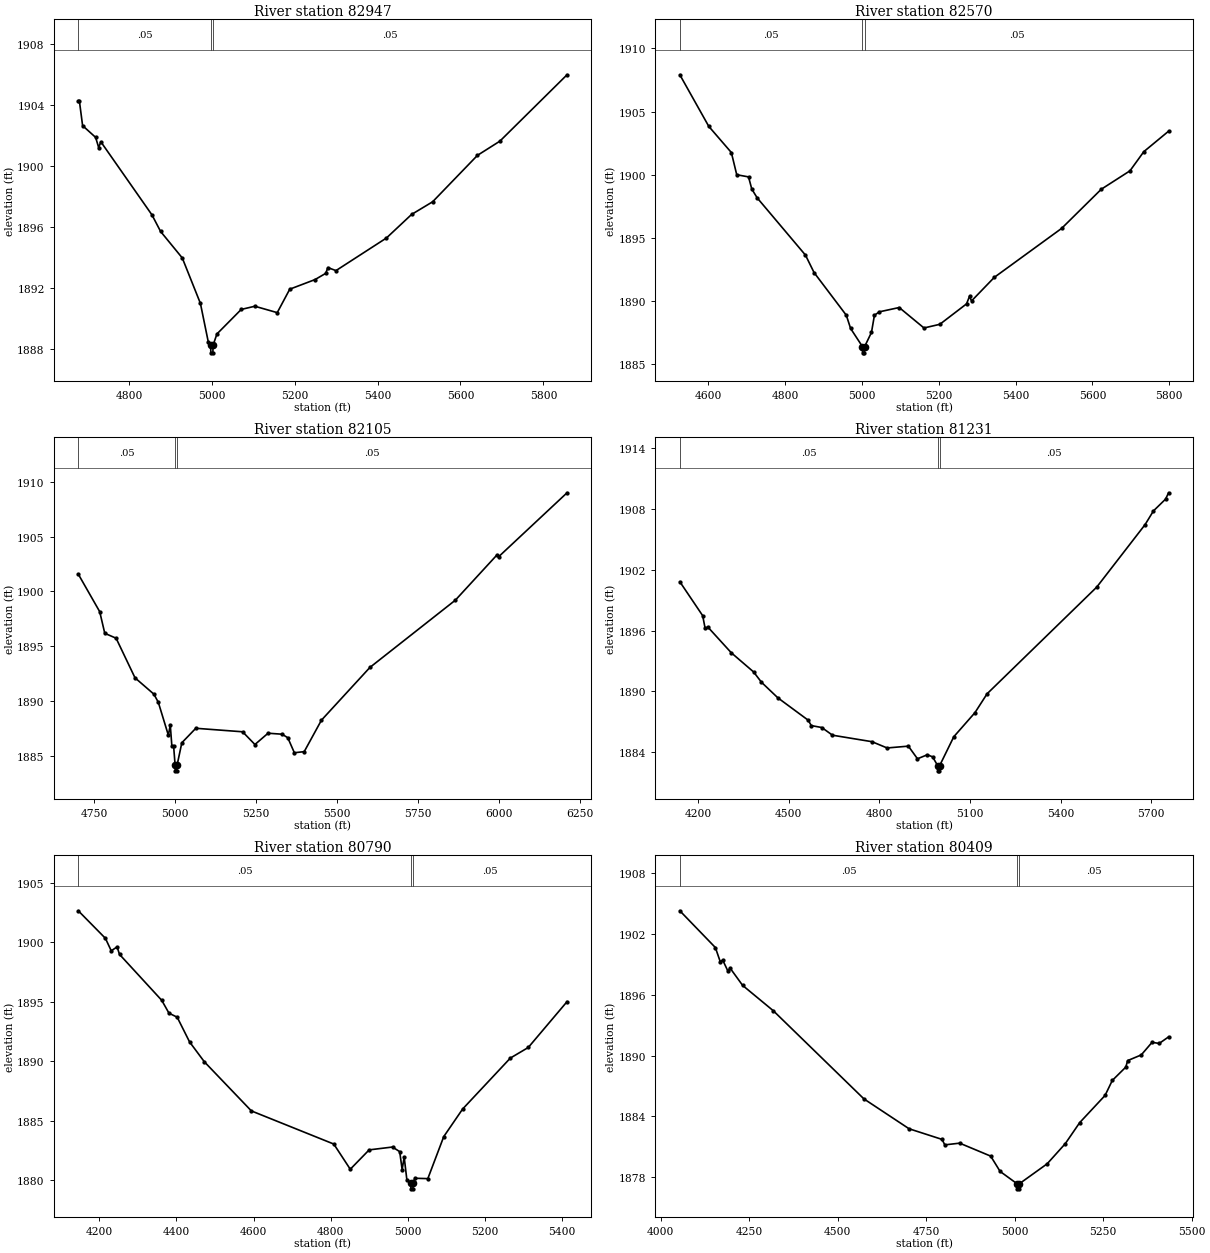
Type RM Length L Ch R = 1,82947,377,377,377
BEGIN DESCRIPTION:
Long Creek 140.0
END DESCRIPTION:
XS GIS Cut Line= 3
      1661755.04      6899788.01      1662182.39      6899918.36
      1662904.97      6900037.99
#Sta/Elev= 30
  4677.9 1904.30  4680.5 1904.30  4688.3 1902.67  4719.7 1901.90  4727.1 1901.23
  4732.3 1901.61  4855.6 1896.81  4876.5 1895.72  4928.8 1893.98  4972.5 1891.00
  4991.5 1888.47  4997.2 1888.25  4997.7 1887.75  5002.6 1887.75  5003.1 1888.25
  5012.4 1888.99  5071.0 1890.60  5103.8 1890.81  5157.9 1890.39  5188.1 1891.93
  5249.0 1892.56  5274.9 1892.97  5280.0 1893.35  5299.6 1893.15  5421.3 1895.29
  5482.1 1896.84  5532.8 1897.67  5641.0 1900.72  5695.0 1901.65  5857.1 1906.01
#Mann=3,-1,0
  4677.9    0.05       0  4997.2    0.03       0  5003.1    0.05       0
Bank Sta=4997.2,5003.1
Exp/Cntr=0.3,0.1

Type RM Length L Ch R = 1,82570,465,465,465
BEGIN DESCRIPTION:
Long Creek 139.0
END DESCRIPTION:
XS GIS Cut Line= 3
      1661555.04      6900038.02      1661955.00      6900238.00
      1662755.01      6900438.00
#Sta/Elev= 30
  4526.2 1907.91  4601.6 1903.82  4660.3 1901.75  4674.3 1899.99  4705.0 1899.82
  4713.4 1898.86  4727.4 1898.16  4853.2 1893.62  4875.5 1892.24  4959.4 1888.86
  4970.6 1887.81  5001.3 1886.38  5001.8 1885.88  5006.7 1885.88  5007.2 1886.38
  5024.9 1887.50  5032.6 1888.86  5045.5 1889.13  5097.1 1889.47  5161.5 1887.85
  5202.7 1888.14  5272.3 1889.76  5280.0 1890.36  5285.2 1889.99  5344.5 1891.86
  5519.7 1895.74  5622.8 1898.84  5697.5 1900.30  5733.6 1901.82  5798.0 1903.44
#Mann=3,-1,0
  4526.2    0.05       0  5001.3    0.03       0  5007.2    0.05       0
Bank Sta=5001.3,5007.2
Exp/Cntr=0.3,0.1

Type RM Length L Ch R = 1,82105,874,874,874
BEGIN DESCRIPTION:
Long Creek 138.0
END DESCRIPTION:
XS GIS Cut Line= 3
      1661504.96      6900487.97      1661755.00      6900638.00
      1662954.95      6900438.01
#Sta/Elev= 30
  4701.0 1901.57  4767.1 1898.15  4782.7 1896.18  4817.7 1895.73  4876.0 1892.12
  4934.3 1890.63  4947.9 1889.89  4979.0 1886.88  4984.8 1887.83  4989.7 1885.91
  4995.1 1885.91  4999.8 1884.14  5000.2 1883.64  5005.2 1883.64  5005.7 1884.14
  5020.5 1886.20  5063.6 1887.52  5208.0 1887.20  5246.0 1886.04  5286.6 1887.07
  5329.7 1886.98  5347.4 1886.66  5367.7 1885.29  5398.1 1885.39  5451.3 1888.26
  5600.9 1893.07  5864.5 1899.20  5993.7 1903.35  5998.8 1903.18  6209.1 1908.99
#Mann=3,-1,0
  4701.0    0.05       0  4999.8    0.03       0  5005.7    0.05       0
Bank Sta=4999.8,5005.7
Exp/Cntr=0.3,0.1

Type RM Length L Ch R = 1,81231,441,441,441
BEGIN DESCRIPTION:
Long Creek 137.0
END DESCRIPTION:
XS GIS Cut Line= 3
      1661341.86      6900955.65      1662155.00      6901038.00
      1662955.04      6901088.00
#Sta/Elev= 30
  4138.8 1900.83  4214.5 1897.48  4222.4 1896.26  4232.4 1896.33  4309.4 1893.81
  4383.2 1891.92  4409.3 1890.90  4463.6 1889.36  4564.1 1887.15  4574.2 1886.62
  4609.0 1886.43  4644.5 1885.67  4775.2 1885.03  4825.4 1884.41  4895.8 1884.59
  4926.0 1883.34  4958.6 1883.74  4976.1 1883.53  4993.1 1882.65  4993.6 1882.15
  4998.7 1882.15  4999.2 1882.65  5046.3 1885.52  5116.4 1887.90  5156.5 1889.76
  5519.7 1900.30  5680.0 1906.48  5707.6 1907.83  5747.6 1908.99  5757.7 1909.62
#Mann=3,-1,0
  4138.8    0.05       0  4993.1    0.03       0  4999.2    0.05       0
Bank Sta=4993.1,4999.2
Exp/Cntr=0.3,0.1

Type RM Length L Ch R = 1,80790,381,381,381
BEGIN DESCRIPTION:
Long Creek 136.0
END DESCRIPTION:
XS GIS Cut Line= 3
      1661255.00      6901138.00      1662055.00      6901438.00
      1662454.99      6901538.00
#Sta/Elev= 30
  4145.8 1902.66  4216.1 1900.34  4231.2 1899.29  4246.4 1899.62  4252.6 1898.99
  4362.1 1895.12  4380.8 1894.04  4402.1 1893.70  4434.2 1891.62  4472.4 1889.95
  4594.4 1885.81  4808.0 1883.02  4850.7 1880.90  4899.6 1882.53  4960.2 1882.77
  4978.8 1882.38  4985.1 1880.87  4990.4 1881.92  4997.5 1879.97  5007.4 1879.75
  5007.9 1879.25  5013.1 1879.25  5013.6 1879.75  5018.2 1880.14  5051.7 1880.11
  5093.0 1883.65  5141.9 1885.97  5265.6 1890.26  5312.0 1891.15  5412.5 1895.01
#Mann=3,-1,0
  4145.8    0.05       0  5007.4    0.03       0  5013.6    0.05       0
Bank Sta=5007.4,5013.6
Exp/Cntr=0.3,0.1

Type RM Length L Ch R = 1,80409,414,414,414
BEGIN DESCRIPTION:
Long Creek 135.0
END DESCRIPTION:
XS GIS Cut Line= 3
      1661155.03      6901238.02      1661798.91      6901740.49
      1662350.49      6901857.57
#Sta/Elev= 30
  4054.2 1904.29  4154.6 1900.66  4168.3 1899.27  4175.4 1899.42  4189.8 1898.35
  4196.2 1898.63  4231.7 1896.92  4318.3 1894.42  4574.2 1885.72  4701.8 1882.77
  4795.0 1881.72  4802.6 1881.18  4844.7 1881.35  4932.3 1880.07  4958.9 1878.56
  5006.9 1877.34  5007.4 1876.84  5012.7 1876.84  5013.2 1877.34  5091.8 1879.31
  5143.0 1881.30  5183.8 1883.38  5255.4 1886.06  5275.8 1887.54  5314.0 1888.86
  5319.2 1889.50  5357.6 1890.06  5388.3 1891.31  5408.2 1891.19  5434.8 1891.84
#Mann=3,-1,0
  4054.2    0.05       0  5006.9    0.03       0  5013.2    0.05       0
Bank Sta=5006.9,5013.2
Exp/Cntr=0.3,0.1

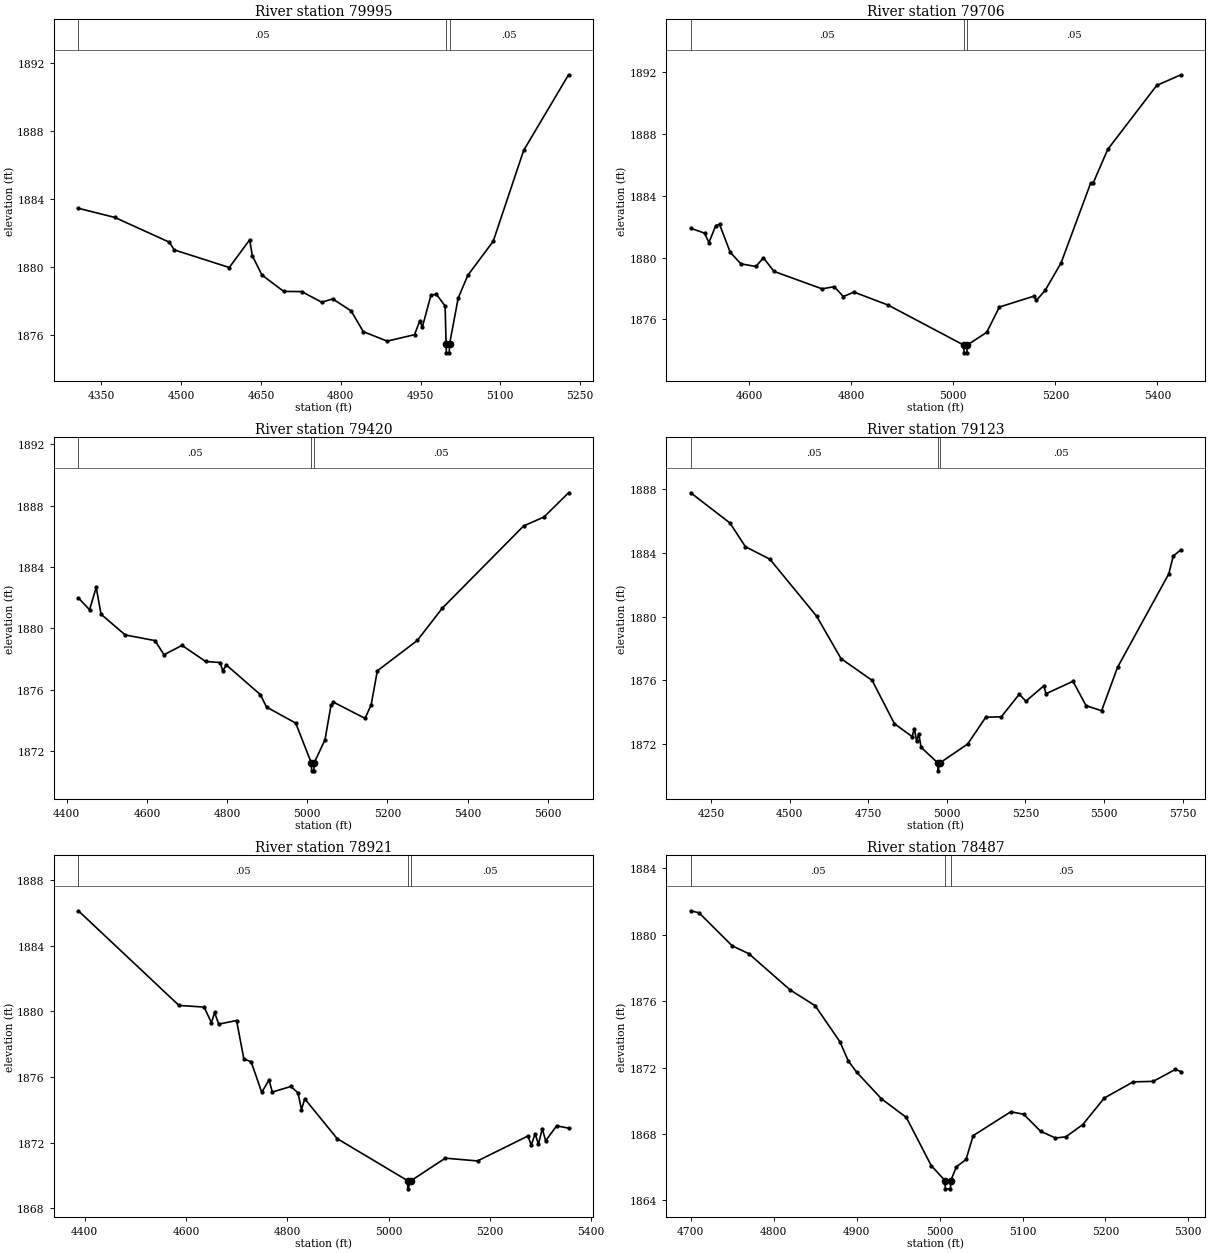
Type RM Length L Ch R = 1,79995,289,289,289
BEGIN DESCRIPTION:
Long Creek 134.0
END DESCRIPTION:
XS GIS Cut Line= 3
      1661257.86      6901963.72      1661782.20      6902078.31
      1662157.17      6902165.11
#Sta/Elev= 30
  4306.7 1883.44  4375.4 1882.90  4477.8 1881.44  4486.8 1880.99  4590.4 1879.95
  4628.7 1881.58  4633.8 1880.64  4651.8 1879.51  4692.7 1878.54  4726.7 1878.53
  4764.4 1877.90  4784.9 1878.10  4819.6 1877.39  4842.3 1876.17  4887.3 1875.61
  4938.7 1875.99  4948.4 1876.79  4953.5 1876.45  4969.5 1878.31  4979.7 1878.38
  4996.2 1877.68  4998.1 1875.42  4998.6 1874.92  5004.0 1874.92  5004.5 1875.42
  5020.8 1878.15  5038.9 1879.49  5086.7 1881.50  5144.0 1886.86  5228.3 1891.31
#Mann=3,-1,0
  4306.7    0.05       0  4998.1    0.03       0  5004.5    0.05       0
Bank Sta=4998.1,5004.5
Exp/Cntr=0.3,0.1

Type RM Length L Ch R = 1,79706,286,286,286
BEGIN DESCRIPTION:
Mapping XS fad66486
END DESCRIPTION:
XS GIS Cut Line= 3
      1661275.24      6902099.13      1661424.56      6902206.78
      1662170.59      6902421.91
#Sta/Elev= 30
  4485.4 1881.90  4512.5 1881.58  4521.1 1880.97  4534.4 1882.07  4541.9 1882.15
  4562.8 1880.34  4583.7 1879.59  4613.1 1879.42  4627.8 1879.98  4648.7 1879.10
  4742.8 1877.97  4766.5 1878.11  4784.4 1877.47  4805.3 1877.76  4872.6 1876.91
  5020.6 1874.32  5021.1 1873.82  5026.5 1873.82  5027.0 1874.32  5065.4 1875.15
  5090.2 1876.79  5157.5 1877.49  5162.7 1877.22  5179.9 1877.87  5211.1 1879.65
  5268.9 1884.81  5274.1 1884.84  5302.5 1887.01  5398.5 1891.16  5445.9 1891.85
#Mann=3,-1,0
  4485.4    0.05       0  5020.6    0.05       0  5027.0    0.05       0
Bank Sta=5020.6,5027
Exp/Cntr=0.3,0.1

Type RM Length L Ch R = 1,79420,297,297,297
BEGIN DESCRIPTION:
Mapping XS 435607c8
END DESCRIPTION:
XS GIS Cut Line= 4
      1661237.68      6902127.56      1661372.21      6902392.28
      1661832.28      6902683.08      1662191.05      6902553.41
#Sta/Elev= 30
  4429.1 1881.98  4457.0 1881.20  4473.6 1882.66  4485.7 1880.91  4546.0 1879.56
  4620.3 1879.19  4642.7 1878.27  4687.6 1878.88  4746.6 1877.83  4783.1 1877.76
  4789.0 1877.22  4798.3 1877.60  4883.1 1875.67  4898.4 1874.86  4971.3 1873.81
  5010.4 1871.20  5010.9 1870.70  5016.5 1870.70  5017.0 1871.20  5044.2 1872.72
  5059.5 1875.01  5065.4 1875.18  5144.2 1874.12  5159.5 1875.01  5174.8 1877.22
  5274.5 1879.20  5337.0 1881.31  5539.8 1886.67  5590.5 1887.25  5651.8 1888.83
#Mann=3,-1,0
  4429.1    0.05       0  5010.4    0.03       0  5017.0    0.05       0
Bank Sta=5010.4,5017
Exp/Cntr=0.3,0.1

Type RM Length L Ch R = 1,79123,202,202,202
BEGIN DESCRIPTION:
Long Creek 133.0
END DESCRIPTION:
XS GIS Cut Line= 3
      1660942.50      6902214.30      1661505.47      6902803.48
      1662079.66      6903277.69
#Sta/Elev= 30
  4185.1 1887.79  4309.8 1885.89  4359.1 1884.40  4437.1 1883.61  4585.6 1880.03
  4663.3 1877.36  4762.3 1875.99  4833.1 1873.27  4889.7 1872.45  4896.6 1872.96
  4903.9 1872.15  4910.8 1872.64  4918.0 1871.78  4971.2 1870.80  4971.7 1870.30
  4978.1 1870.80  5066.4 1871.99  5123.7 1873.67  5173.2 1873.70  5230.6 1875.12
  5251.4 1874.68  5308.8 1875.65  5315.2 1875.15  5401.3 1875.93  5442.9 1874.40
  5492.4 1874.08  5543.3 1876.82  5706.1 1882.69  5720.4 1883.81  5744.7 1884.21
#Mann=3,-1,0
  4185.1    0.05       0  4971.2    0.03       0  4978.1    0.05       0
Bank Sta=4971.2,4978.1
Exp/Cntr=0.3,0.1

Type RM Length L Ch R = 1,78921,434,434,434
BEGIN DESCRIPTION:
Long Creek 132.0
END DESCRIPTION:
XS GIS Cut Line= 3
      1660925.17      6902578.92      1661406.93      6902960.86
      1661670.58      6903195.91
#Sta/Elev= 30
  4387.4 1886.13  4586.1 1880.36  4635.7 1880.26  4650.1 1879.31  4656.5 1879.93
  4664.6 1879.22  4699.8 1879.44  4714.2 1877.10  4728.7 1876.92  4749.5 1875.06
  4763.9 1875.82  4770.3 1875.08  4807.2 1875.42  4821.1 1875.03  4828.0 1874.01
  4834.4 1874.67  4898.5 1872.24  5037.5 1869.68  5038.0 1869.18  5044.5 1869.68
  5112.0 1871.05  5175.6 1870.88  5275.1 1872.40  5281.8 1871.85  5289.3 1872.53
  5296.0 1871.91  5303.5 1872.84  5310.2 1872.11  5331.9 1873.02  5355.4 1872.88
#Mann=3,-1,0
  4387.4    0.05       0  5037.5    0.03       0  5044.5    0.05       0
Bank Sta=5037.5,5044.5
Exp/Cntr=0.3,0.1

Type RM Length L Ch R = 1,78487,470,470,470
BEGIN DESCRIPTION:
Long Creek 131.0
END DESCRIPTION:
XS GIS Cut Line= 3
      1661055.05      6903338.00      1661355.00      6903338.00
      1661641.64      6903286.94
#Sta/Elev= 30
  4699.9 1881.44  4709.9 1881.32  4749.9 1879.33  4769.9 1878.86  4819.9 1876.67
  4849.9 1875.73  4879.9 1873.55  4889.9 1872.40  4899.9 1871.73  4929.9 1870.12
  4959.9 1869.00  4989.9 1866.10  5006.5 1865.20  5007.0 1864.70  5013.1 1864.70
  5013.6 1865.20  5020.2 1866.02  5031.9 1866.47  5040.5 1867.90  5085.8 1869.34
  5101.4 1869.19  5121.7 1868.17  5139.7 1867.76  5152.2 1867.83  5172.5 1868.56
  5198.7 1870.17  5233.5 1871.14  5257.7 1871.17  5284.3 1871.89  5291.0 1871.76
#Mann=3,-1,0
  4699.9    0.05       0  5006.5    0.03       0  5013.6    0.05       0
Bank Sta=5006.5,5013.6
Exp/Cntr=0.3,0.1

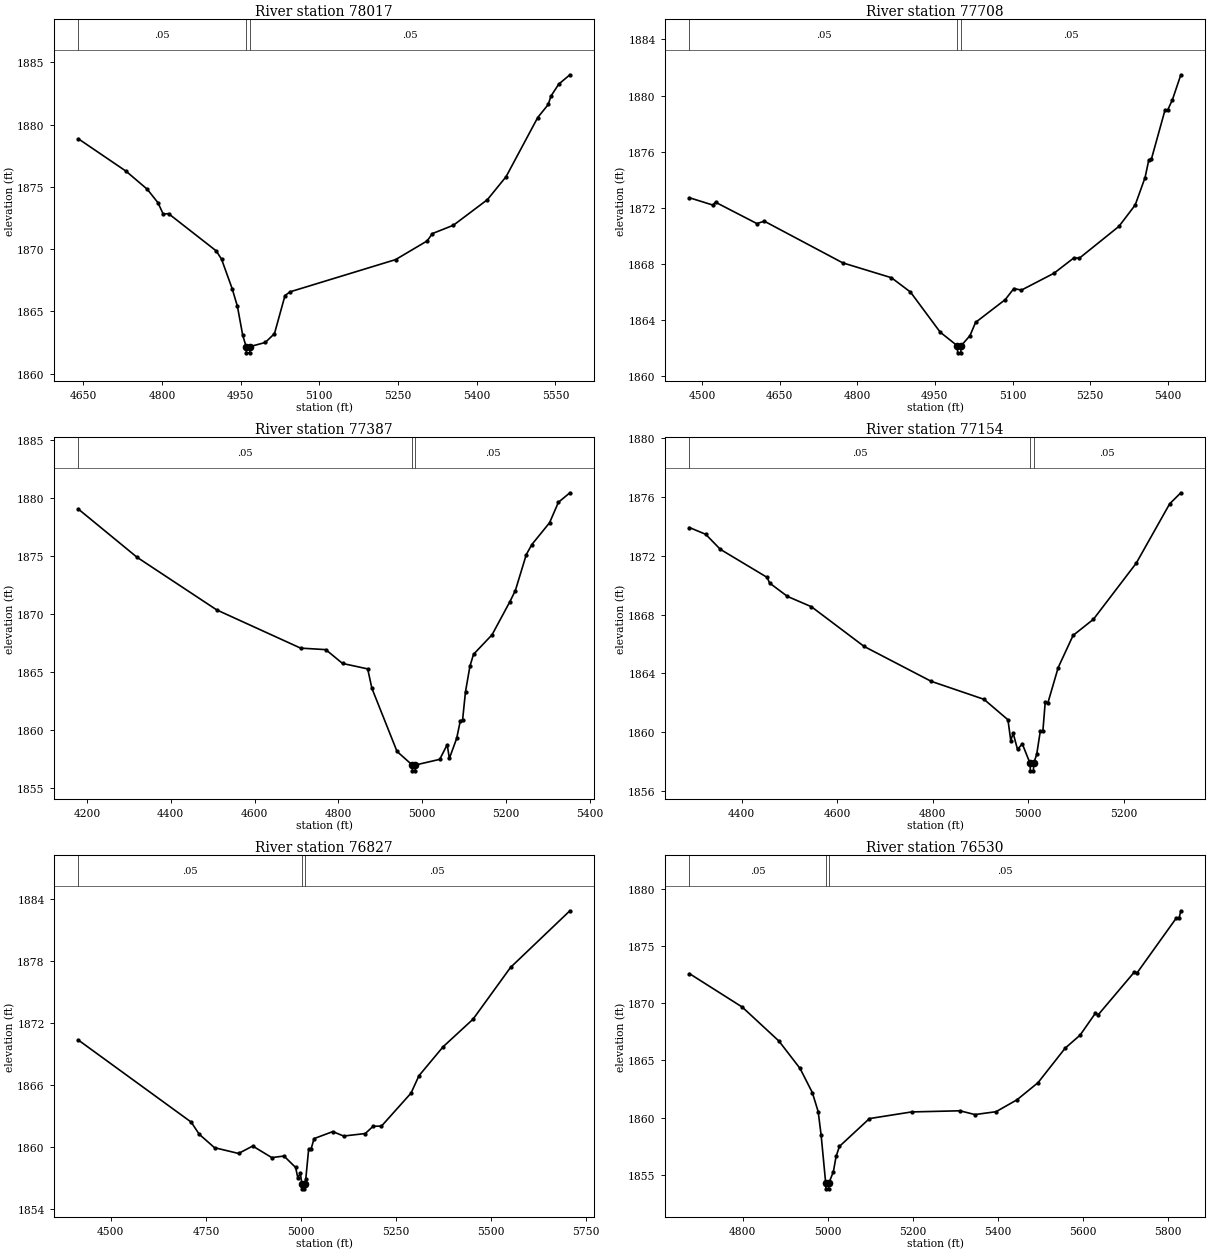
Type RM Length L Ch R = 1,78017,309,309,309
BEGIN DESCRIPTION:
Long Creek 130.0
END DESCRIPTION:
XS GIS Cut Line= 3
      1661205.03      6903688.00      1661555.00      6903738.00
      1662136.10      6903690.03
#Sta/Elev= 30
  4640.9 1878.85  4731.8 1876.25  4772.2 1874.80  4792.4 1873.73  4802.5 1872.81
  4812.6 1872.85  4903.5 1869.86  4913.6 1869.20  4933.8 1866.84  4943.9 1865.41
  4954.0 1863.09  4960.5 1862.18  4961.0 1861.68  4967.2 1861.68  4967.7 1862.18
  4996.9 1862.51  5014.5 1863.22  5034.6 1866.28  5044.6 1866.58  5245.3 1869.16
  5305.5 1870.66  5315.5 1871.25  5355.6 1871.92  5420.3 1873.97  5456.0 1875.82
  5516.2 1880.56  5536.3 1881.61  5541.3 1882.27  5556.3 1883.24  5577.5 1883.99
#Mann=3,-1,0
  4640.9    0.05       0  4960.5    0.03       0  4967.7    0.05       0
Bank Sta=4960.5,4967.7
Exp/Cntr=0.3,0.1

Type RM Length L Ch R = 1,77708,321,321,321
BEGIN DESCRIPTION:
Mapping XS 66adf0dc
END DESCRIPTION:
XS GIS Cut Line= 2
      1661181.49      6904179.01      1662080.41      6903873.58
#Sta/Elev= 30
  4475.8 1872.72  4521.0 1872.20  4526.3 1872.40  4606.2 1870.88  4620.5 1871.05
  4772.1 1868.08  4866.2 1867.02  4902.9 1866.00  4960.4 1863.14  4993.5 1862.17
  4994.0 1861.67  5000.2 1861.67  5000.7 1862.17  5017.9 1862.90  5028.7 1863.84
  5085.9 1865.46  5102.6 1866.25  5117.3 1866.14  5180.1 1867.34  5218.8 1868.44
  5229.4 1868.42  5305.6 1870.68  5337.0 1872.20  5356.1 1874.16  5363.1 1875.38
  5368.4 1875.48  5394.5 1878.95  5399.8 1878.97  5408.9 1879.70  5425.2 1881.48
#Mann=3,-1,0
  4475.8    0.05       0  4993.5    0.03       0  5000.7    0.05       0
Bank Sta=4993.5,5000.7
Exp/Cntr=0.3,0.1

Type RM Length L Ch R = 1,77387,233,233,233
BEGIN DESCRIPTION:
Long Creek 129.0
END DESCRIPTION:
XS GIS Cut Line= 3
      1660954.97      6904288.00      1661813.45      6904310.95
      1662111.00      6904210.61
#Sta/Elev= 30
  4179.8 1879.03  4319.9 1874.88  4509.9 1870.35  4710.0 1867.06  4770.0 1866.93
  4810.1 1865.74  4870.1 1865.27  4880.1 1863.60  4940.1 1858.16  4976.5 1856.99
  4977.0 1856.49  4983.2 1856.49  4983.7 1856.99  5042.0 1857.48  5059.8 1858.74
  5065.0 1857.56  5082.4 1859.28  5091.2 1860.81  5096.5 1860.86  5103.5 1863.31
  5114.1 1865.51  5122.7 1866.53  5166.9 1868.21  5209.1 1871.04  5222.4 1872.01
  5248.6 1875.12  5261.8 1875.98  5304.1 1877.86  5325.2 1879.62  5352.6 1880.44
#Mann=3,-1,0
  4179.8    0.05       0  4976.5    0.03       0  4983.7    0.05       0
Bank Sta=4976.5,4983.7
Exp/Cntr=0.3,0.1

Type RM Length L Ch R = 1,77154,327,327,327
BEGIN DESCRIPTION:
Long Creek 128.0
END DESCRIPTION:
XS GIS Cut Line= 3
      1661120.49      6904479.96      1661855.00      6904538.00
      1662105.04      6904387.98
#Sta/Elev= 30
  4290.7 1873.91  4324.8 1873.45  4355.4 1872.43  4453.5 1870.52  4458.5 1870.14
  4495.9 1869.23  4546.0 1868.53  4656.4 1865.83  4796.8 1863.46  4907.1 1862.24
  4957.3 1860.85  4963.2 1859.44  4968.2 1859.94  4977.3 1858.84  4987.4 1859.21
  5003.7 1857.88  5004.2 1857.38  5010.6 1857.38  5011.1 1857.88  5017.5 1858.50
  5025.0 1860.08  5030.4 1860.08  5035.3 1862.04  5041.1 1862.02  5062.5 1864.40
  5093.6 1866.58  5136.3 1867.68  5225.8 1871.49  5295.7 1875.52  5319.1 1876.27
#Mann=3,-1,0
  4290.7    0.05       0  5003.7    0.03       0  5011.1    0.05       0
Bank Sta=5003.7,5011.1
Exp/Cntr=0.3,0.1

Type RM Length L Ch R = 1,76827,297,297,297
BEGIN DESCRIPTION:
Long Creek 127.0
END DESCRIPTION:
XS GIS Cut Line= 3
      1661298.44      6904918.32      1661862.66      6904870.58
      1662405.01      6904387.99
#Sta/Elev= 30
  4414.9 1870.35  4711.4 1862.40  4732.6 1861.22  4772.7 1859.92  4835.9 1859.36
  4873.1 1860.08  4923.3 1858.96  4955.4 1859.11  4986.0 1858.00  4991.7 1857.00
  4998.4 1857.42  5002.3 1856.43  5002.8 1855.93  5009.2 1855.93  5009.7 1856.43
  5012.7 1856.88  5020.2 1859.76  5026.9 1859.82  5034.4 1860.80  5083.7 1861.48
  5112.2 1861.05  5169.0 1861.29  5189.9 1862.00  5211.7 1862.01  5289.4 1865.21
  5310.3 1866.90  5373.9 1869.71  5452.5 1872.38  5551.1 1877.40  5707.1 1882.89
#Mann=3,-1,0
  4414.9    0.05       0  5002.3    0.05       0  5009.7    0.05       0
Bank Sta=5002.3,5009.7
Exp/Cntr=0.3,0.1

Type RM Length L Ch R = 1,76530,343,343,343
BEGIN DESCRIPTION:
Mapping XS 5d426861
END DESCRIPTION:
XS GIS Cut Line= 3
      1661507.86      6905286.67      1661934.98      6904946.36
      1662354.63      6904502.43
#Sta/Elev= 30
  4674.2 1872.58  4798.6 1869.66  4885.1 1866.69  4934.8 1864.30  4963.6 1862.20
  4977.4 1860.54  4984.4 1858.47  4995.1 1854.30  4995.6 1853.80  5002.1 1853.80
  5002.6 1854.30  5013.2 1855.30  5019.6 1856.64  5027.6 1857.51  5098.1 1859.93
  5197.4 1860.51  5311.2 1860.61  5346.4 1860.28  5396.2 1860.53  5445.5 1861.57
  5494.9 1863.06  5558.8 1866.07  5594.0 1867.21  5629.6 1869.10  5636.5 1868.98
  5721.4 1872.70  5728.3 1872.65  5820.6 1877.43  5827.4 1877.47  5831.2 1878.06
#Mann=3,-1,0
  4674.2    0.05       0  4995.1    0.03       0  5002.6    0.05       0
Bank Sta=4995.1,5002.6
Exp/Cntr=0.3,0.1