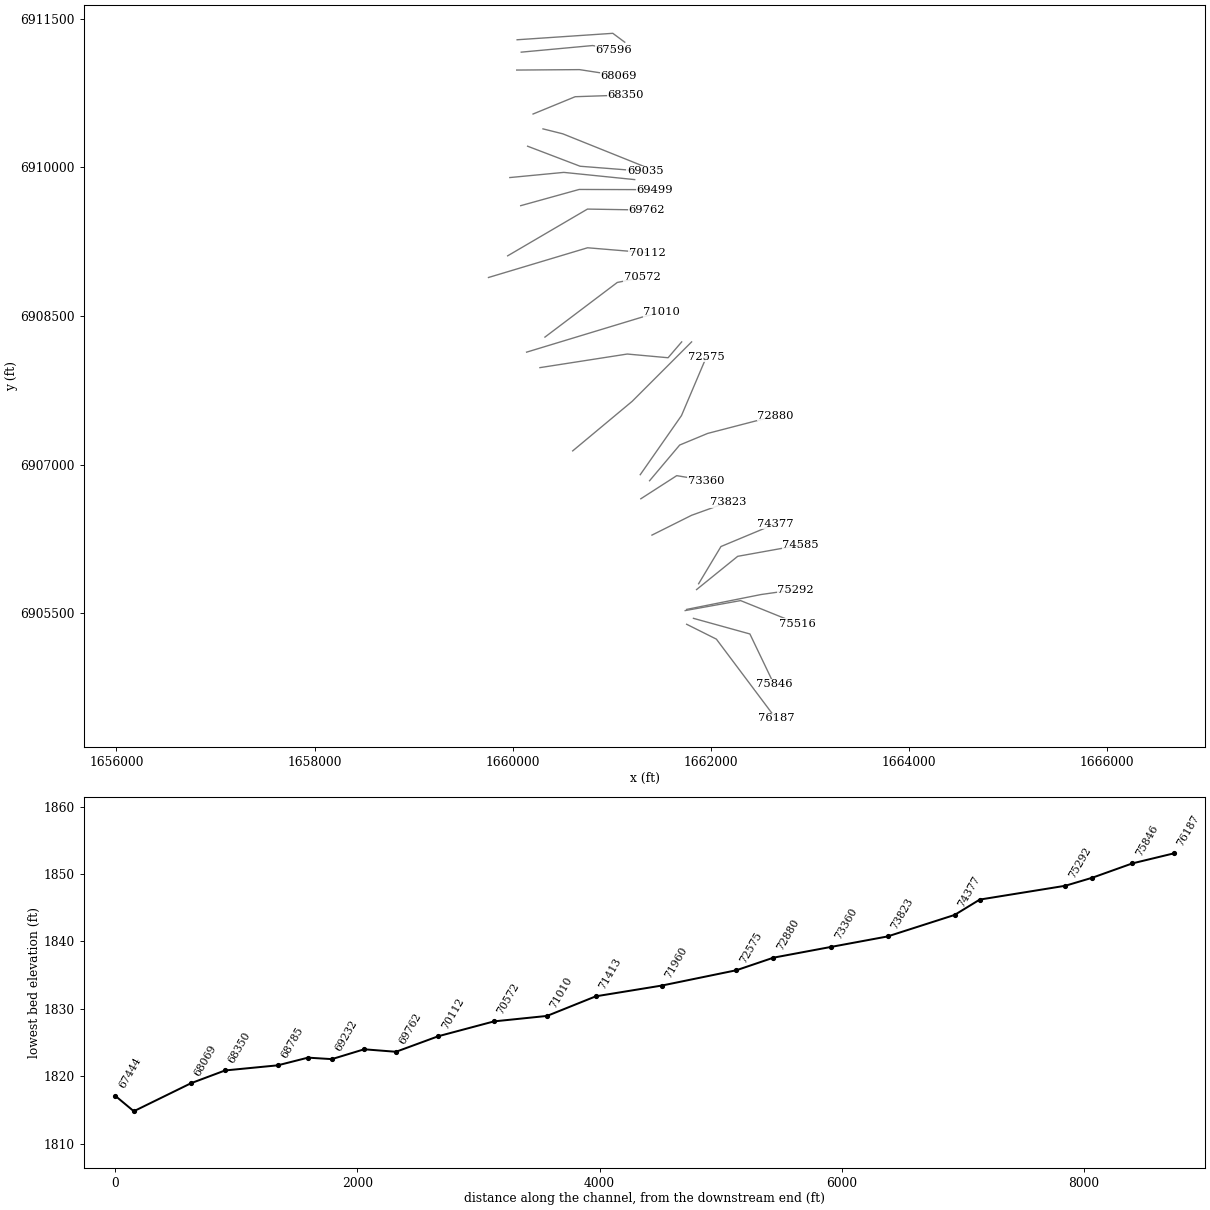
HEC-RAS study Long Creek.prj: Long Creek Base Level Engineering

--- Long Creek.g01 (geometry) --- (continued)

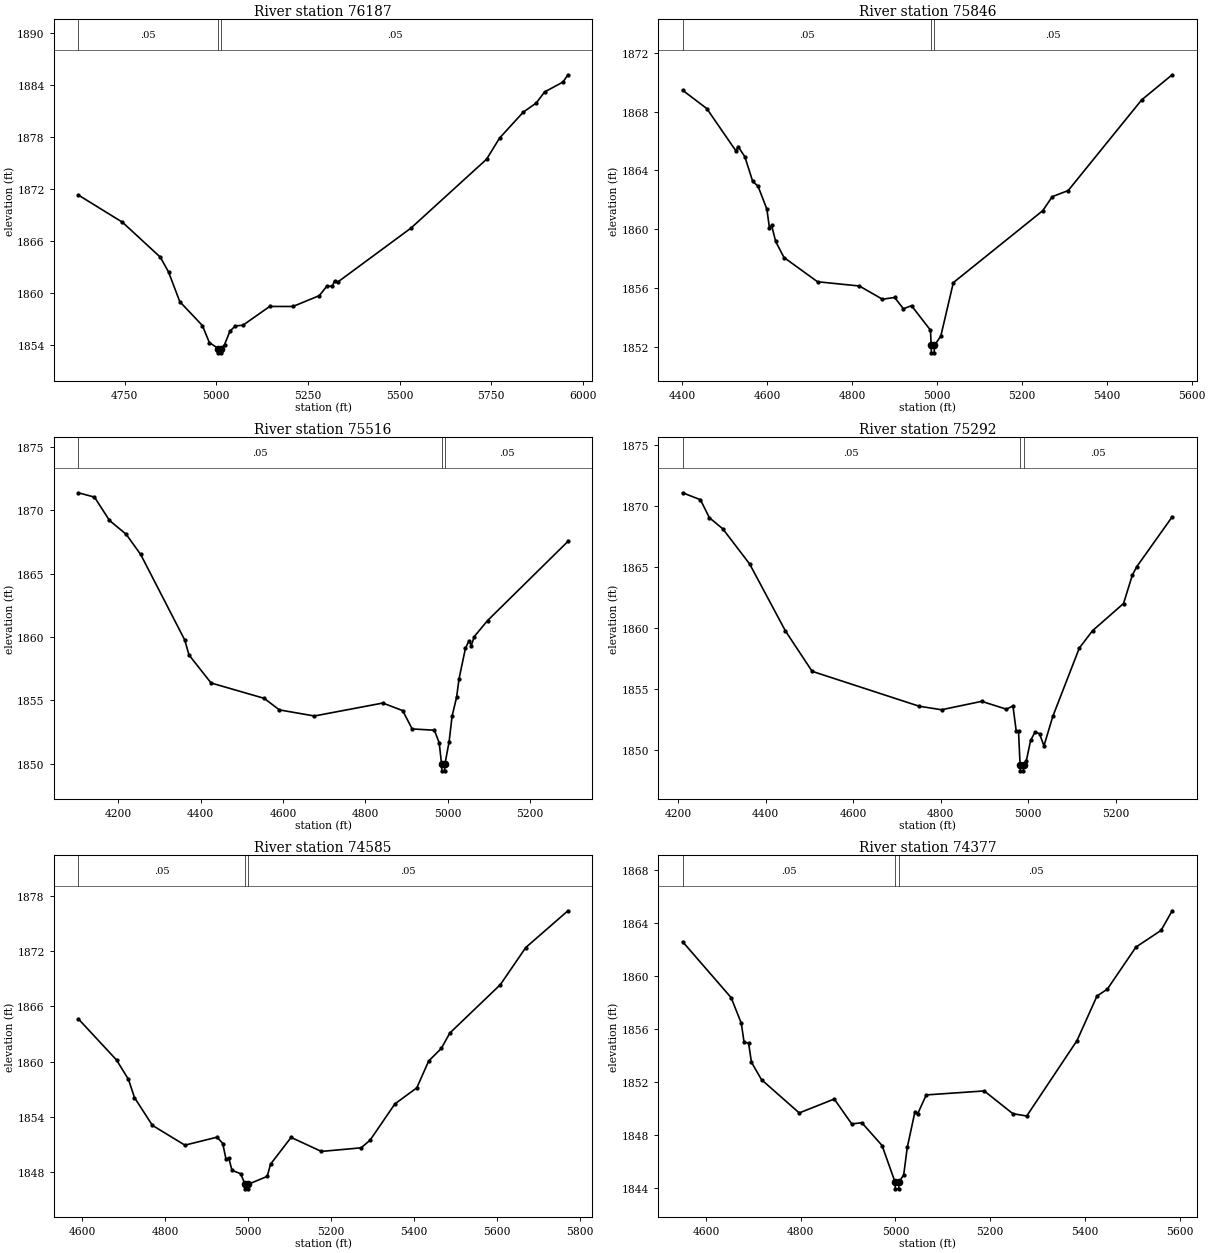
Type RM Length L Ch R = 1,76187,341,341,341
BEGIN DESCRIPTION:
Long Creek 126.0
END DESCRIPTION:
XS GIS Cut Line= 3
      1661755.00      6905388.00      1662055.00      6905238.00
      1662655.00      6904438.00
#Sta/Elev= 30
  4623.6 1871.30  4743.8 1868.16  4847.2 1864.12  4869.6 1862.41  4900.3 1858.98
  4962.1 1856.21  4980.9 1854.25  5005.3 1853.56  5005.8 1853.06  5012.3 1853.06
  5012.8 1853.56  5022.5 1854.01  5037.1 1855.56  5051.7 1856.17  5072.5 1856.25
  5145.5 1858.42  5209.0 1858.42  5280.9 1859.67  5301.7 1860.78  5316.3 1860.76
  5322.5 1861.35  5330.9 1861.23  5530.9 1867.48  5737.1 1875.44  5772.5 1877.88
  5837.1 1880.88  5872.5 1881.93  5895.5 1883.22  5945.5 1884.36  5959.0 1885.20
#Mann=3,-1,0
  4623.6    0.05       0  5005.3    0.05       0  5012.8    0.05       0
Bank Sta=5005.3,5012.8
Exp/Cntr=0.3,0.1

Type RM Length L Ch R = 1,75846,330,330,330
BEGIN DESCRIPTION:
Long Creek 125.0
END DESCRIPTION:
XS GIS Cut Line= 3
      1661823.63      6905447.83      1662393.31      6905290.11
      1662636.36      6904783.18
#Sta/Elev= 30
  4400.8 1869.46  4457.8 1868.21  4526.4 1865.33  4531.6 1865.62  4547.5 1864.93
  4565.9 1863.26  4578.6 1862.92  4599.4 1861.36  4605.4 1860.09  4610.6 1860.25
  4620.1 1859.16  4639.7 1858.07  4718.7 1856.42  4817.3 1856.13  4871.5 1855.23
  4900.3 1855.35  4921.0 1854.58  4940.1 1854.79  4984.8 1853.12  4986.4 1852.08
  4986.9 1851.58  4993.5 1851.58  4994.0 1852.08  5009.1 1852.72  5038.6 1856.36
  5249.3 1861.26  5271.5 1862.21  5309.2 1862.63  5482.2 1868.80  5554.1 1870.51
#Mann=3,-1,0
  4400.8    0.05       0  4986.4    0.05       0  4994.0    0.05       0
Bank Sta=4986.4,4994
Exp/Cntr=0.3,0.1

Type RM Length L Ch R = 1,75516,224,224,224
BEGIN DESCRIPTION:
Mapping XS 817792d2
END DESCRIPTION:
XS GIS Cut Line= 3
      1661740.52      6905526.22      1662299.56      6905626.92
      1662875.95      6905394.28
#Sta/Elev= 30
  4103.0 1871.36  4142.2 1871.02  4178.7 1869.18  4219.3 1868.09  4254.5 1866.50
  4361.6 1859.76  4371.8 1858.59  4425.5 1856.38  4554.6 1855.17  4591.4 1854.26
  4676.5 1853.78  4842.9 1854.80  4891.2 1854.20  4914.1 1852.76  4968.1 1852.66
  4979.8 1851.67  4985.7 1849.96  4986.2 1849.46  4993.1 1849.46  4993.6 1849.96
  5004.0 1851.77  5011.2 1853.78  5022.0 1855.24  5028.1 1856.72  5043.6 1859.11
  5052.3 1859.71  5057.6 1859.32  5065.1 1860.04  5097.5 1861.30  5292.6 1867.53
#Mann=3,-1,0
  4103.0    0.05       0  4985.7    0.03       0  4993.6    0.05       0
Bank Sta=4985.7,4993.6
Exp/Cntr=0.3,0.1

Type RM Length L Ch R = 1,75292,707,707,707
BEGIN DESCRIPTION:
Long Creek 124.0
END DESCRIPTION:
XS GIS Cut Line= 3
      1661754.96      6905537.99      1662505.00      6905688.00
      1662854.96      6905737.99
#Sta/Elev= 30
  4210.3 1871.11  4251.1 1870.54  4271.5 1869.06  4302.1 1868.15  4363.3 1865.27
  4444.9 1859.78  4506.1 1856.44  4750.8 1853.57  4801.8 1853.28  4893.6 1853.97
  4949.7 1853.33  4965.0 1853.58  4972.6 1851.50  4977.7 1851.50  4981.3 1848.76
  4981.8 1848.26  4988.7 1848.26  4989.2 1848.76  4995.4 1849.06  5005.5 1850.78
  5015.6 1851.45  5025.7 1851.31  5035.8 1850.31  5056.0 1852.73  5116.6 1858.35
  5146.9 1859.78  5217.6 1862.01  5237.8 1864.35  5247.9 1865.04  5328.7 1869.13
#Mann=3,-1,0
  4210.3    0.05       0  4981.3    0.03       0  4989.2    0.05       0
Bank Sta=4981.3,4989.2
Exp/Cntr=0.3,0.1

Type RM Length L Ch R = 1,74585,208,208,208
BEGIN DESCRIPTION:
Long Creek 123.0
END DESCRIPTION:
XS GIS Cut Line= 3
      1661855.00      6905738.00      1662270.27      6906073.82
      1662905.02      6906188.00
#Sta/Elev= 30
  4591.4 1864.65  4683.4 1860.19  4712.1 1858.09  4726.5 1856.12  4769.7 1853.10
  4848.0 1850.95  4925.8 1851.82  4939.2 1851.12  4947.1 1849.41  4953.6 1849.55
  4961.5 1848.22  4982.3 1847.85  4992.7 1846.71  4993.2 1846.21  5000.2 1846.21
  5000.7 1846.71  5046.3 1847.56  5054.2 1848.88  5103.8 1851.79  5176.6 1850.27
  5272.5 1850.66  5294.1 1851.50  5353.8 1855.43  5406.5 1857.17  5435.1 1860.08
  5465.6 1861.45  5485.9 1863.11  5607.8 1868.37  5668.8 1872.39  5770.4 1876.38
#Mann=3,-1,0
  4591.4    0.05       0  4992.7    0.03       0  5000.7    0.05       0
Bank Sta=4992.7,5000.7
Exp/Cntr=0.3,0.1

Type RM Length L Ch R = 1,74377,554,554,554
BEGIN DESCRIPTION:
Long Creek 122.0
END DESCRIPTION:
XS GIS Cut Line= 3
      1661875.97      6905797.09      1662101.38      6906172.66
      1662651.29      6906402.15
#Sta/Elev= 30
  4550.6 1862.59  4653.2 1858.36  4674.6 1856.43  4680.4 1855.01  4690.1 1854.91
  4696.0 1853.49  4717.3 1852.17  4797.0 1849.66  4870.9 1850.71  4907.8 1848.83
  4929.2 1848.92  4971.9 1847.20  4999.4 1844.43  4999.9 1843.93  5006.9 1843.93
  5007.4 1844.43  5017.6 1844.99  5025.1 1847.06  5041.4 1849.76  5046.8 1849.57
  5065.2 1851.02  5187.6 1851.32  5248.2 1849.60  5277.4 1849.43  5383.5 1855.12
  5425.7 1858.48  5447.7 1859.01  5508.0 1862.18  5561.1 1863.44  5584.5 1864.92
#Mann=3,-1,0
  4550.6    0.05       0  4999.4    0.05       0  5007.4    0.05       0
Bank Sta=4999.4,5007.4
Exp/Cntr=0.3,0.1

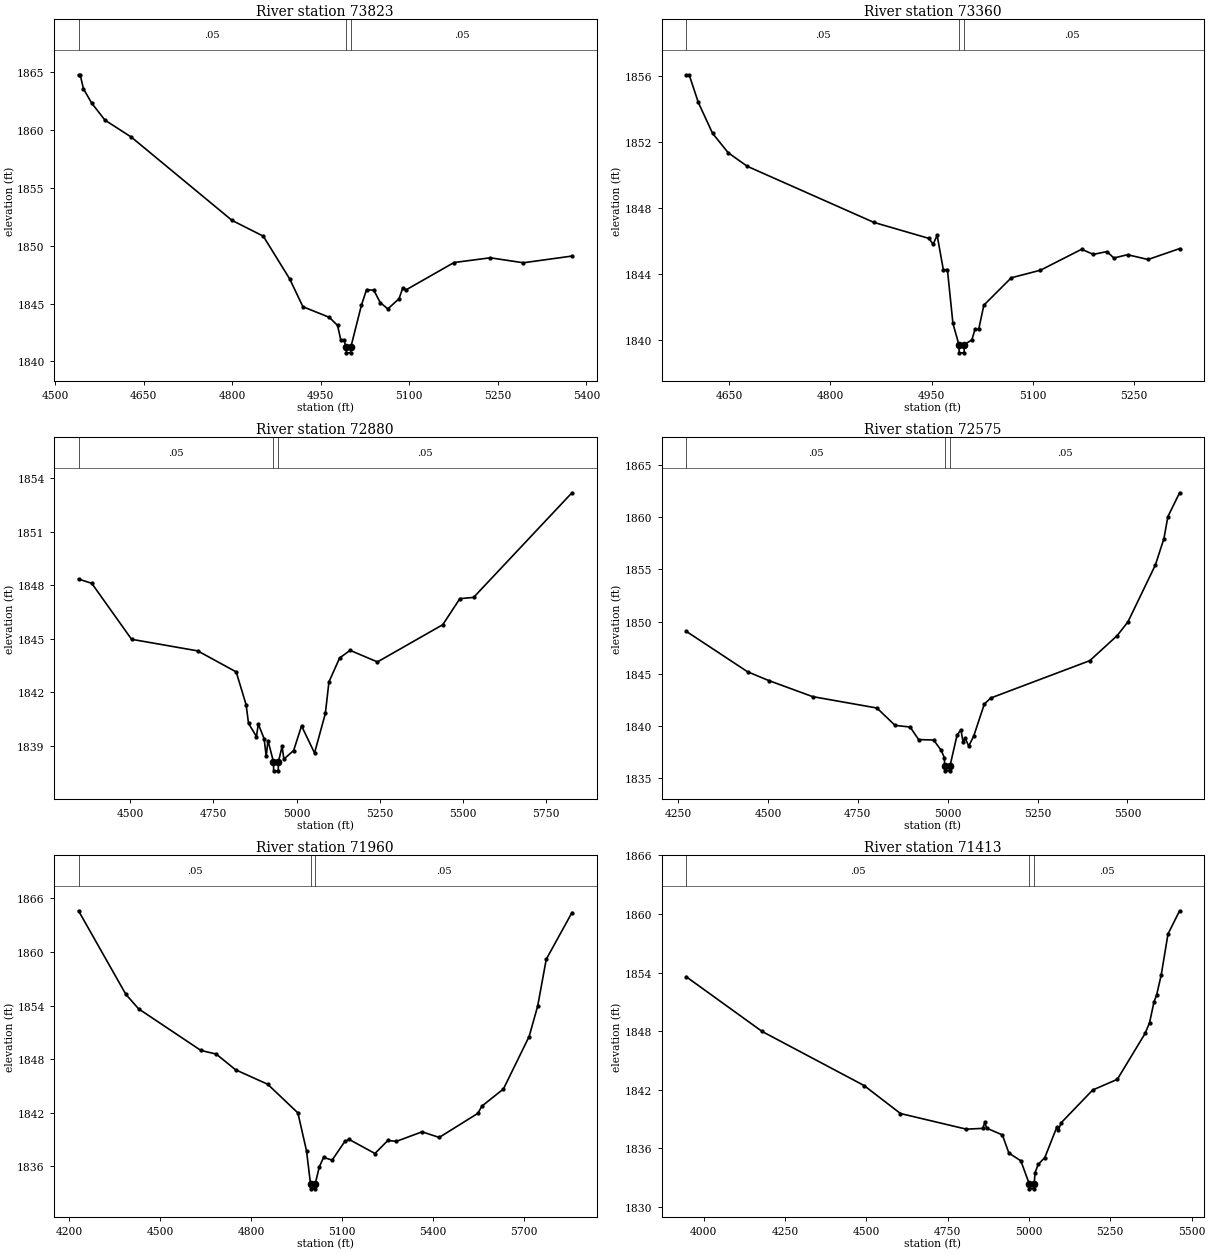
Type RM Length L Ch R = 1,73823,463,463,463
BEGIN DESCRIPTION:
Long Creek 121.0
END DESCRIPTION:
XS GIS Cut Line= 3
      1661405.03      6906288.01      1661805.00      6906488.00
      1662170.58      6906619.79
#Sta/Elev= 30
  4539.7 1864.79  4542.5 1864.79  4548.1 1863.57  4562.0 1862.34  4584.4 1860.87
  4629.1 1859.40  4799.6 1852.20  4852.7 1850.83  4897.4 1847.13  4919.8 1844.73
  4964.5 1843.81  4978.5 1843.11  4984.1 1841.81  4989.5 1841.81  4992.9 1841.24
  4993.4 1840.74  5000.5 1840.74  5001.0 1841.24  5018.8 1844.84  5027.6 1846.21
  5040.0 1846.15  5050.7 1845.09  5063.6 1844.54  5082.6 1845.42  5089.0 1846.36
  5094.3 1846.18  5175.7 1848.55  5237.1 1848.96  5293.2 1848.53  5375.5 1849.11
#Mann=3,-1,0
  4539.7    0.05       0  4992.9    0.03       0  5001.0    0.05       0
Bank Sta=4992.9,5001
Exp/Cntr=0.3,0.1

Type RM Length L Ch R = 1,73360,480,480,480
BEGIN DESCRIPTION:
Long Creek 120.0
END DESCRIPTION:
XS GIS Cut Line= 3
      1661292.61      6906654.70      1661655.00      6906888.00
      1661951.17      6906838.92
#Sta/Elev= 30
  4586.3 1856.06  4590.7 1856.06  4604.3 1854.38  4625.4 1852.51  4648.6 1851.33
  4676.9 1850.51  4864.4 1847.11  4945.9 1846.14  4952.3 1845.78  4958.2 1846.33
  4967.4 1844.23  4973.4 1844.25  4981.6 1840.98  4990.4 1839.70  4990.9 1839.20
  4998.1 1839.20  4998.6 1839.70  5009.7 1839.99  5014.3 1840.63  5019.8 1840.63
  5027.4 1842.09  5068.0 1843.75  5111.3 1844.21  5172.3 1845.48  5189.6 1845.17
  5209.9 1845.34  5220.0 1844.95  5240.3 1845.15  5270.7 1844.86  5317.5 1845.52
#Mann=3,-1,0
  4586.3    0.05       0  4990.4    0.03       0  4998.6    0.05       0
Bank Sta=4990.4,4998.6
Exp/Cntr=0.3,0.1

Type RM Length L Ch R = 1,72880,305,305,305
BEGIN DESCRIPTION:
Mapping XS c37a4433
END DESCRIPTION:
XS GIS Cut Line= 4
      1661380.86      6906836.70      1661684.71      6907196.97
      1661966.83      6907314.16      1662651.27      6907491.77
#Sta/Elev= 30
  4344.1 1848.35  4383.9 1848.11  4503.6 1844.97  4702.5 1844.32  4818.3 1843.14
  4848.2 1841.29  4855.4 1840.25  4879.3 1839.51  4884.7 1840.22  4902.3 1839.39
  4908.5 1838.41  4913.9 1839.29  4930.4 1838.09  4930.9 1837.59  4944.7 1837.59
  4945.2 1838.09  4956.3 1838.96  4961.7 1838.25  4991.0 1838.73  5014.8 1840.11
  5053.9 1838.59  5086.4 1840.81  5097.2 1842.58  5129.3 1843.92  5160.8 1844.35
  5243.0 1843.70  5439.6 1845.79  5490.9 1847.25  5532.2 1847.32  5828.0 1853.19
#Mann=3,-1,0
  4344.1    0.05       0  4930.4    0.03       0  4945.2    0.05       0
Bank Sta=4930.4,4945.2
Exp/Cntr=0.3,0.1

Type RM Length L Ch R = 1,72575,615,615,615
BEGIN DESCRIPTION:
Long Creek 119.0
END DESCRIPTION:
XS GIS Cut Line= 3
      1661286.69      6906897.71      1661702.84      6907494.19
      1661954.99      6908087.97
#Sta/Elev= 30
  4272.7 1849.08  4443.8 1845.20  4502.2 1844.37  4624.3 1842.83  4803.1 1841.74
  4853.7 1840.08  4895.6 1839.92  4919.2 1838.72  4961.0 1838.68  4982.0 1837.69
  4990.7 1836.99  4991.8 1836.23  4992.3 1835.73  5006.2 1835.73  5006.7 1836.23
  5025.9 1839.12  5036.7 1839.66  5043.0 1838.47  5048.5 1838.88  5058.5 1838.10
  5072.1 1839.02  5101.9 1842.11  5119.4 1842.69  5395.3 1846.27  5471.3 1848.66
  5501.4 1849.98  5577.8 1855.43  5601.5 1857.95  5612.5 1860.05  5645.1 1862.33
#Mann=3,-1,0
  4272.7    0.05       0  4991.8    0.03       0  5006.7    0.05       0
Bank Sta=4991.8,5006.7
Exp/Cntr=0.3,0.1

Type RM Length L Ch R = 1,71960,547,547,547
BEGIN DESCRIPTION:
Long Creek 118.0
END DESCRIPTION:
XS GIS Cut Line= 3
      1660605.04      6907138.03      1661205.00      6907638.00
      1661805.00      6908238.00
#Sta/Elev= 30
  4229.9 1864.62  4386.1 1855.26  4428.4 1853.63  4634.0 1848.97  4684.8 1848.56
  4748.6 1846.80  4854.7 1845.18  4954.3 1841.97  4982.9 1837.71  4996.2 1833.96
  4996.7 1833.46  5010.7 1833.46  5011.2 1833.96  5025.0 1835.91  5039.2 1836.98
  5067.4 1836.68  5109.9 1838.80  5124.0 1838.99  5208.9 1837.42  5251.3 1838.88
  5279.6 1838.78  5364.4 1839.85  5421.0 1839.22  5548.3 1841.91  5562.4 1842.74
  5633.1 1844.65  5718.0 1850.53  5746.3 1853.95  5774.6 1859.19  5859.4 1864.41
#Mann=3,-1,0
  4229.9    0.05       0  4996.2    0.03       0  5011.2    0.05       0
Bank Sta=4996.2,5011.2
Exp/Cntr=0.3,0.1

Type RM Length L Ch R = 1,71413,403,403,403
BEGIN DESCRIPTION:
Long Creek 117.0
END DESCRIPTION:
XS GIS Cut Line= 4
      1660274.16      6907978.23      1661155.68      6908115.49
      1661567.52      6908078.05      1661705.00      6908238.00
#Sta/Elev= 30
  3946.5 1853.58  4180.1 1847.97  4493.1 1842.44  4605.2 1839.57  4807.6 1837.97
  4858.0 1838.05  4864.6 1838.68  4869.6 1838.08  4918.3 1837.38  4938.4 1835.52
  4975.1 1834.73  5001.1 1832.36  5001.6 1831.86  5015.7 1831.86  5016.2 1832.36
  5018.7 1833.51  5028.7 1834.37  5048.8 1835.06  5085.5 1838.16  5090.5 1837.86
  5099.0 1838.62  5196.0 1841.98  5271.6 1843.07  5357.2 1847.78  5370.8 1848.88
  5384.6 1851.03  5392.3 1851.68  5406.6 1853.76  5427.4 1857.95  5463.1 1860.33
#Mann=3,-1,0
  3946.5    0.05       0  5001.1    0.05       0  5016.2    0.05       0
Bank Sta=5001.1,5016.2
Exp/Cntr=0.3,0.1

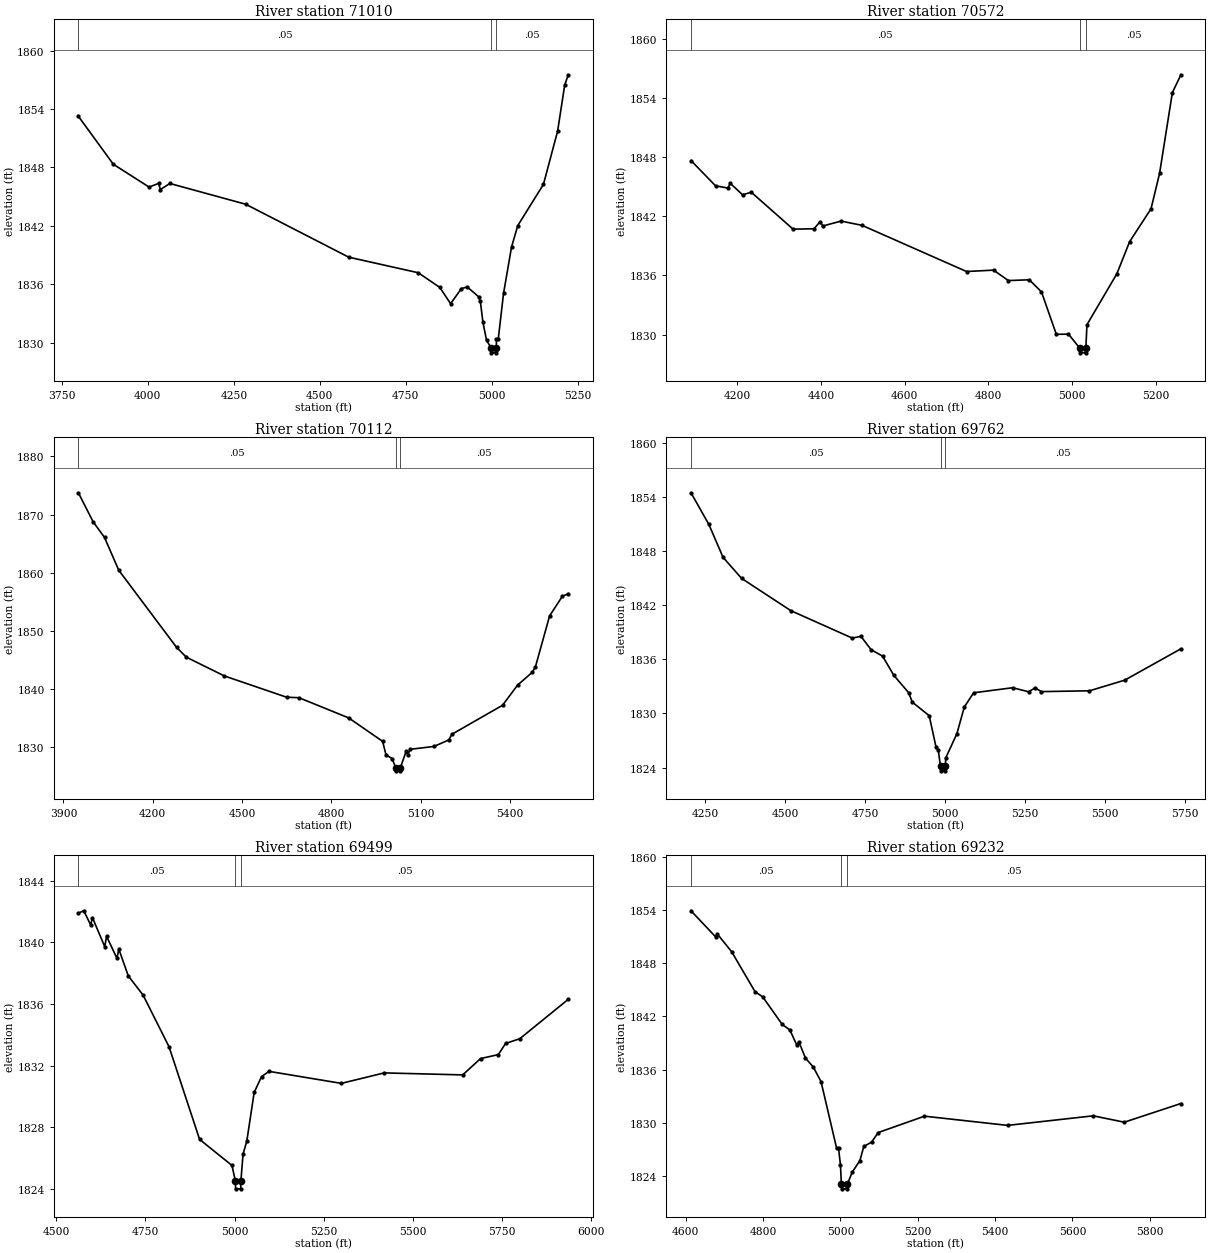
Type RM Length L Ch R = 1,71010,438,438,438
BEGIN DESCRIPTION:
Long Creek 116.0
END DESCRIPTION:
XS GIS Cut Line= 3
      1660139.55      6908134.46      1661305.00      6908488.00
      1661505.05      6908538.01
#Sta/Elev= 30
  3798.1 1853.26  3899.7 1848.33  4003.7 1845.98  4031.3 1846.36  4036.6 1845.73
  4064.2 1846.35  4284.5 1844.22  4583.9 1838.78  4786.1 1837.18  4848.8 1835.67
  4880.1 1834.00  4911.5 1835.55  4928.5 1835.72  4961.4 1834.72  4966.6 1834.23
  4974.2 1832.07  4984.6 1830.24  4998.0 1829.45  4998.5 1828.95  5012.6 1828.95
  5013.1 1829.45  5013.4 1830.34  5018.6 1830.34  5034.0 1835.05  5057.2 1839.81
  5075.3 1842.02  5150.0 1846.26  5191.2 1851.73  5211.8 1856.47  5222.2 1857.52
#Mann=3,-1,0
  3798.1    0.05       0  4998.0    0.05       0  5013.1    0.05       0
Bank Sta=4998,5013.1
Exp/Cntr=0.3,0.1

Type RM Length L Ch R = 1,70572,460,460,460
BEGIN DESCRIPTION:
Long Creek 115.0
END DESCRIPTION:
XS GIS Cut Line= 3
      1660324.76      6908286.42      1661055.00      6908838.00
      1661305.00      6908888.00
#Sta/Elev= 30
  4089.6 1847.67  4148.3 1845.10  4177.4 1844.88  4183.7 1845.35  4212.8 1844.19
  4233.6 1844.45  4333.5 1840.70  4383.5 1840.74  4398.1 1841.47  4404.3 1841.02
  4448.0 1841.52  4498.0 1841.09  4747.7 1836.40  4812.2 1836.54  4847.6 1835.48
  4897.6 1835.56  4926.7 1834.33  4962.1 1830.02  4991.2 1830.04  5017.6 1828.64
  5018.1 1828.14  5032.2 1828.14  5032.7 1828.64  5035.3 1831.00  5106.7 1836.17
  5137.3 1839.44  5188.3 1842.77  5208.7 1846.36  5239.3 1854.58  5259.7 1856.38
#Mann=3,-1,0
  4089.6    0.05       0  5017.6    0.05       0  5032.7    0.05       0
Bank Sta=5017.6,5032.7
Exp/Cntr=0.3,0.1

Type RM Length L Ch R = 1,70112,350,350,350
BEGIN DESCRIPTION:
Long Creek 114.0
END DESCRIPTION:
XS GIS Cut Line= 3
      1659754.99      6908888.00      1660755.00      6909188.00
      1661354.98      6909138.00
#Sta/Elev= 30
  3950.0 1873.74  3999.6 1868.76  4037.9 1866.06  4085.7 1860.43  4279.8 1847.18
  4312.8 1845.48  4440.7 1842.25  4649.5 1838.60  4691.3 1838.51  4858.3 1835.04
  4972.3 1831.01  4983.6 1828.69  5004.1 1828.06  5016.5 1826.44  5017.0 1825.94
  5031.3 1825.94  5031.8 1826.44  5051.7 1829.35  5056.8 1828.63  5064.3 1829.64
  5144.6 1830.13  5194.7 1831.25  5204.8 1832.22  5375.4 1837.22  5425.5 1840.66
  5475.7 1842.91  5485.7 1843.82  5533.4 1852.58  5576.1 1855.94  5596.1 1856.40
#Mann=3,-1,0
  3950.0    0.05       0  5016.5    0.05       0  5031.8    0.05       0
Bank Sta=5016.5,5031.8
Exp/Cntr=0.3,0.1

Type RM Length L Ch R = 1,69762,263,263,263
BEGIN DESCRIPTION:
Mapping XS 3d97d6f6
END DESCRIPTION:
XS GIS Cut Line= 3
      1659948.60      6909106.69      1660753.89      6909578.48
      1661350.49      6909568.62
#Sta/Elev= 30
  4206.1 1854.48  4261.9 1850.97  4306.2 1847.32  4364.2 1844.98  4518.0 1841.40
  4709.6 1838.36  4736.9 1838.55  4768.3 1837.08  4804.6 1836.35  4839.4 1834.23
  4885.6 1832.31  4897.3 1831.25  4950.0 1829.75  4971.5 1826.24  4978.4 1825.91
  4985.3 1824.13  4985.8 1823.63  5000.1 1823.63  5000.6 1824.13  5001.6 1825.06
  5036.4 1827.74  5059.6 1830.71  5088.8 1832.29  5210.5 1832.85  5260.5 1832.40
  5280.5 1832.83  5300.6 1832.42  5450.6 1832.51  5560.6 1833.69  5736.1 1837.17
#Mann=3,-1,0
  4206.1    0.05       0  4985.3    0.05       0  5000.6    0.05       0
Bank Sta=4985.3,5000.6
Exp/Cntr=0.3,0.1

Type RM Length L Ch R = 1,69499,267,267,267
BEGIN DESCRIPTION:
Mapping XS a87af47b
END DESCRIPTION:
XS GIS Cut Line= 3
      1660080.14      6909612.88      1660670.24      6909776.54
      1661430.87      6909774.35
#Sta/Elev= 30
  4562.3 1841.91  4577.7 1842.06  4596.7 1841.14  4601.9 1841.61  4636.2 1839.73
  4641.4 1840.40  4670.5 1838.97  4675.7 1839.57  4702.2 1837.83  4743.8 1836.58
  4816.4 1833.23  4902.1 1827.21  4992.8 1825.52  5002.4 1824.50  5002.9 1824.00
  5017.3 1824.00  5017.8 1824.50  5023.9 1826.26  5034.3 1827.09  5055.1 1830.27
  5075.8 1831.29  5096.6 1831.63  5299.4 1830.85  5419.4 1831.53  5639.4 1831.40
  5689.4 1832.46  5739.4 1832.72  5759.4 1833.44  5799.4 1833.75  5935.3 1836.31
#Mann=3,-1,0
  4562.3    0.05       0  5002.4    0.05       0  5017.8    0.05       0
Bank Sta=5002.4,5017.8
Exp/Cntr=0.3,0.1

Type RM Length L Ch R = 1,69232,197,197,197
BEGIN DESCRIPTION:
Mapping XS ebd25633
END DESCRIPTION:
XS GIS Cut Line= 3
      1659970.33      6909896.63      1660515.06      6909948.82
      1661230.63      6909875.97
#Sta/Elev= 30
  4613.8 1853.92  4677.2 1850.99  4682.2 1851.28  4718.9 1849.30  4779.2 1844.80
  4799.3 1844.20  4849.5 1841.10  4869.6 1840.46  4887.5 1838.74  4892.5 1839.15
  4909.8 1837.29  4929.9 1836.29  4950.0 1834.64  4990.1 1827.15  4995.2 1827.13
  5000.2 1825.23  5002.6 1823.04  5003.1 1822.54  5017.5 1822.54  5018.0 1823.04
  5030.4 1824.41  5050.5 1825.73  5060.5 1827.32  5080.6 1827.81  5097.8 1828.89
  5217.4 1830.74  5432.4 1829.70  5653.5 1830.78  5733.9 1830.06  5880.3 1832.17
#Mann=3,-1,0
  4613.8    0.05       0  5002.6    0.05       0  5018.0    0.05       0
Bank Sta=5002.6,5018
Exp/Cntr=0.3,0.1

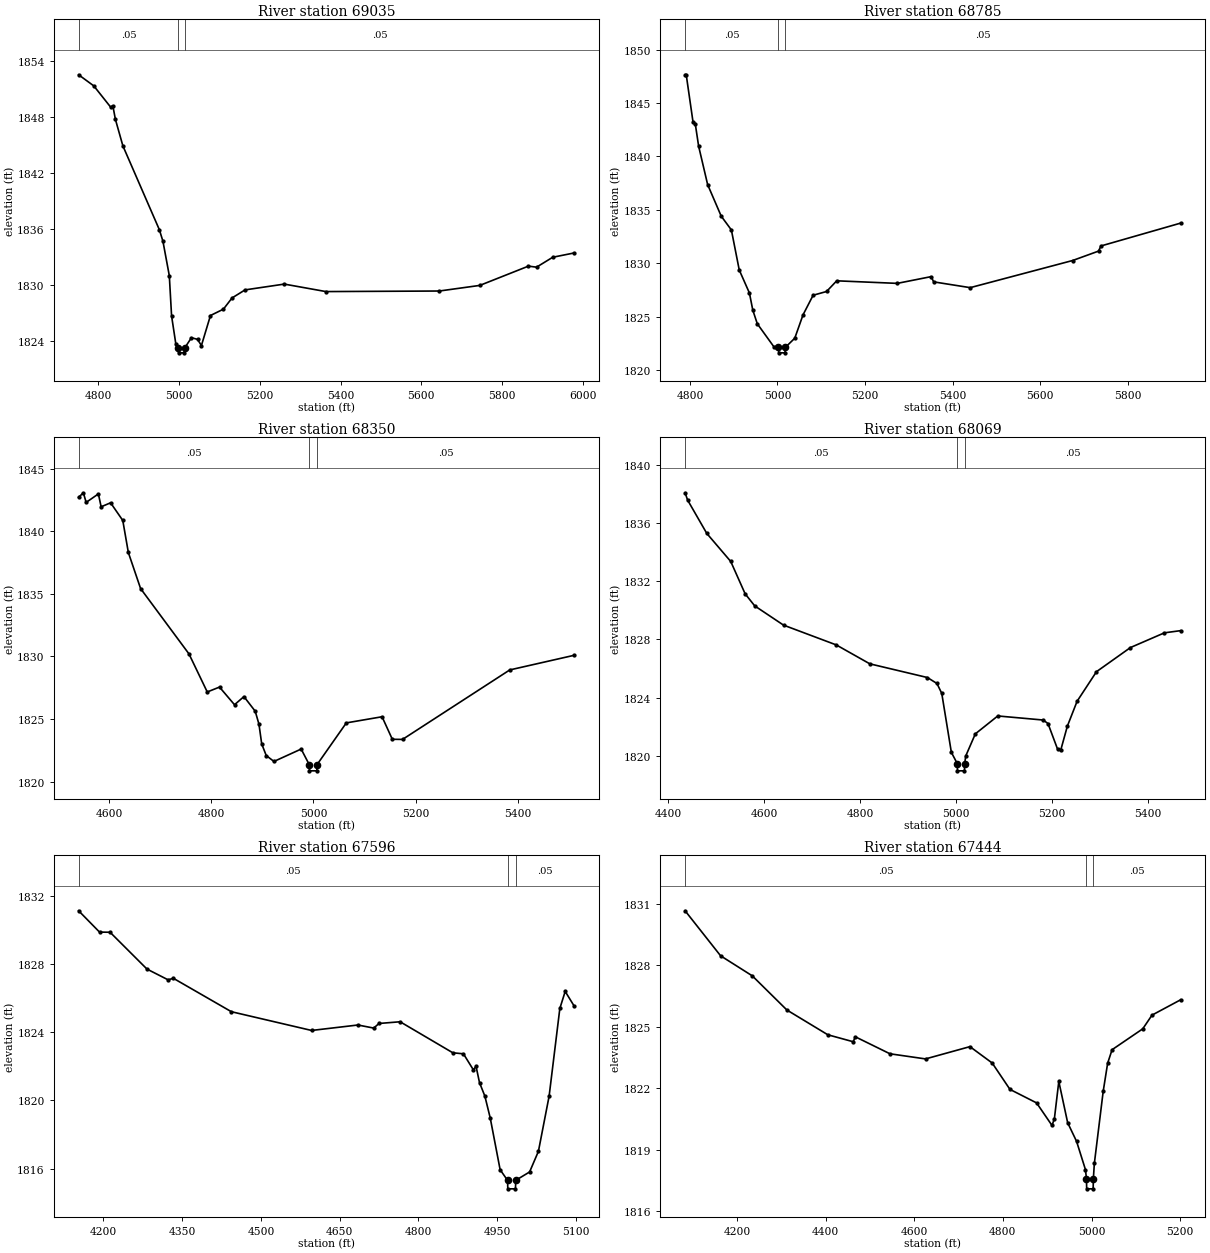
Type RM Length L Ch R = 1,69035,250,250,250
BEGIN DESCRIPTION:
Mapping XS 629f0d50
END DESCRIPTION:
XS GIS Cut Line= 3
      1660149.91      6910212.95      1660679.91      6910010.79
      1661337.95      6909959.24
#Sta/Elev= 30
  4751.2 1852.49  4788.8 1851.30  4830.7 1849.02  4836.1 1849.14  4842.3 1847.72
  4860.8 1844.89  4951.1 1835.93  4960.0 1834.69  4975.8 1831.01  4981.4 1826.71
  4992.1 1823.66  4998.2 1823.26  4998.7 1822.76  5013.1 1822.76  5013.6 1823.26
  5030.6 1824.38  5045.6 1824.20  5055.3 1823.54  5077.7 1826.75  5109.8 1827.43
  5131.2 1828.63  5163.4 1829.49  5260.6 1830.11  5363.7 1829.31  5644.5 1829.37
  5744.8 1829.97  5865.2 1832.03  5885.3 1831.92  5925.4 1832.98  5978.5 1833.44
#Mann=3,-1,0
  4751.2    0.05       0  4998.2    0.05       0  5013.6    0.05       0
Bank Sta=4998.2,5013.6
Exp/Cntr=0.3,0.1

Type RM Length L Ch R = 1,68785,435,435,435
BEGIN DESCRIPTION:
Long Creek 113.0
END DESCRIPTION:
XS GIS Cut Line= 3
      1660304.99      6910388.00      1660505.00      6910338.00
      1661363.98      6909993.11
#Sta/Elev= 30
  4789.0 1847.64  4791.6 1847.64  4807.0 1843.25  4812.2 1843.06  4819.9 1840.96
  4840.5 1837.36  4871.5 1834.41  4894.7 1833.12  4912.7 1829.37  4935.9 1827.22
  4943.6 1825.62  4953.9 1824.34  4992.6 1822.14  5002.3 1822.12  5002.8 1821.62
  5017.2 1821.62  5017.7 1822.12  5039.5 1822.99  5058.3 1825.17  5081.4 1827.01
  5112.1 1827.36  5135.3 1828.36  5273.5 1828.12  5350.8 1828.75  5356.8 1828.26
  5440.2 1827.72  5674.1 1830.26  5733.3 1831.14  5738.7 1831.62  5920.8 1833.76
#Mann=3,-1,0
  4789.0    0.05       0  5002.3    0.05       0  5017.7    0.05       0
Bank Sta=5002.3,5017.7
Exp/Cntr=0.3,0.1

Type RM Length L Ch R = 1,68350,281,281,281
BEGIN DESCRIPTION:
Long Creek 112.0
END DESCRIPTION:
XS GIS Cut Line= 3
      1660204.99      6910538.00      1660630.02      6910712.60
      1661141.14      6910729.92
#Sta/Elev= 30
  4539.9 1842.71  4549.2 1843.07  4554.6 1842.30  4578.6 1842.98  4584.0 1841.95
  4602.5 1842.27  4626.4 1840.86  4637.3 1838.30  4661.3 1835.42  4756.1 1830.20
  4791.9 1827.16  4815.9 1827.55  4845.3 1826.14  4863.8 1826.79  4885.9 1825.62
  4893.2 1824.59  4898.6 1823.01  4907.5 1822.08  4922.6 1821.61  4975.9 1822.60
  4991.7 1821.36  4992.2 1820.86  5006.6 1820.86  5007.1 1821.36  5064.4 1824.69
  5134.4 1825.18  5154.5 1823.38  5174.5 1823.37  5384.6 1828.92  5510.8 1830.09
#Mann=3,-1,0
  4539.9    0.05       0  4991.7    0.05       0  5007.1    0.05       0
Bank Sta=4991.7,5007.1
Exp/Cntr=0.3,0.1

Type RM Length L Ch R = 1,68069,473,473,473
BEGIN DESCRIPTION:
Mapping XS 172525cd
END DESCRIPTION:
XS GIS Cut Line= 3
      1660039.77      6910981.69      1660673.42      6910986.03
      1661068.41      6910925.27
#Sta/Elev= 30
  4435.2 1838.07  4440.4 1837.57  4480.4 1835.28  4530.4 1833.35  4560.4 1831.13
  4580.4 1830.30  4640.4 1828.98  4750.4 1827.62  4820.4 1826.32  4940.4 1825.38
  4960.4 1824.97  4970.4 1824.29  4990.4 1820.24  5002.7 1819.47  5003.2 1818.97
  5017.7 1818.97  5018.2 1819.47  5020.4 1819.99  5040.4 1821.51  5087.2 1822.74
  5181.8 1822.46  5191.9 1822.22  5212.1 1820.44  5218.8 1820.43  5232.3 1822.04
  5252.6 1823.75  5293.0 1825.78  5363.9 1827.44  5434.7 1828.45  5468.5 1828.60
#Mann=3,-1,0
  4435.2    0.05       0  5002.7    0.03       0  5018.2    0.05       0
Bank Sta=5002.7,5018.2
Exp/Cntr=0.3,0.1

Type RM Length L Ch R = 1,67596,152,152,152
BEGIN DESCRIPTION:
Mapping XS c3df777c
END DESCRIPTION:
XS GIS Cut Line= 3
      1660085.35      6911162.36      1660806.52      6911229.12
      1661021.80      6911186.07
#Sta/Elev= 30
  4152.7 1831.12  4192.5 1829.87  4212.6 1829.86  4282.9 1827.70  4323.1 1827.07
  4333.1 1827.16  4443.6 1825.20  4596.4 1824.10  4684.6 1824.42  4714.7 1824.24
  4724.8 1824.51  4765.0 1824.61  4865.4 1822.79  4885.6 1822.73  4904.5 1821.79
  4909.6 1822.00  4916.2 1821.04  4926.4 1820.25  4936.6 1818.97  4955.5 1815.93
  4969.6 1815.31  4970.1 1814.81  4984.7 1814.81  4985.2 1815.31  5011.6 1815.80
  5028.4 1817.01  5048.8 1820.25  5069.2 1825.39  5079.4 1826.39  5096.5 1825.53
#Mann=3,-1,0
  4152.7    0.05       0  4969.6    0.05       0  4985.2    0.05       0
Bank Sta=4969.6,4985.2
Exp/Cntr=0.3,0.1

Type RM Length L Ch R = 1,67444,405,405,405
BEGIN DESCRIPTION:
Long Creek 111.0
END DESCRIPTION:
XS GIS Cut Line= 3
      1660043.71      6911287.37      1661009.85      6911352.47
      1661129.97      6911263.02
#Sta/Elev= 30
  4083.0 1830.67  4163.1 1828.47  4234.6 1827.49  4312.7 1825.82  4405.0 1824.61
  4462.2 1824.27  4467.2 1824.51  4545.3 1823.68  4625.5 1823.43  4725.7 1824.03
  4775.9 1823.23  4816.0 1821.94  4876.1 1821.28  4910.8 1820.18  4916.2 1820.50
  4926.2 1822.33  4946.2 1820.31  4966.3 1819.40  4986.3 1818.02  4988.6 1817.58
  4989.1 1817.08  5003.7 1817.08  5004.2 1817.58  5006.4 1818.32  5026.4 1821.85
  5036.4 1823.22  5046.4 1823.88  5115.6 1824.90  5136.5 1825.57  5201.1 1826.32
#Mann=3,-1,0
  4083.0    0.05       0  4988.6    0.05       0  5004.2    0.05       0
Bank Sta=4988.6,5004.2
Exp/Cntr=0.3,0.1