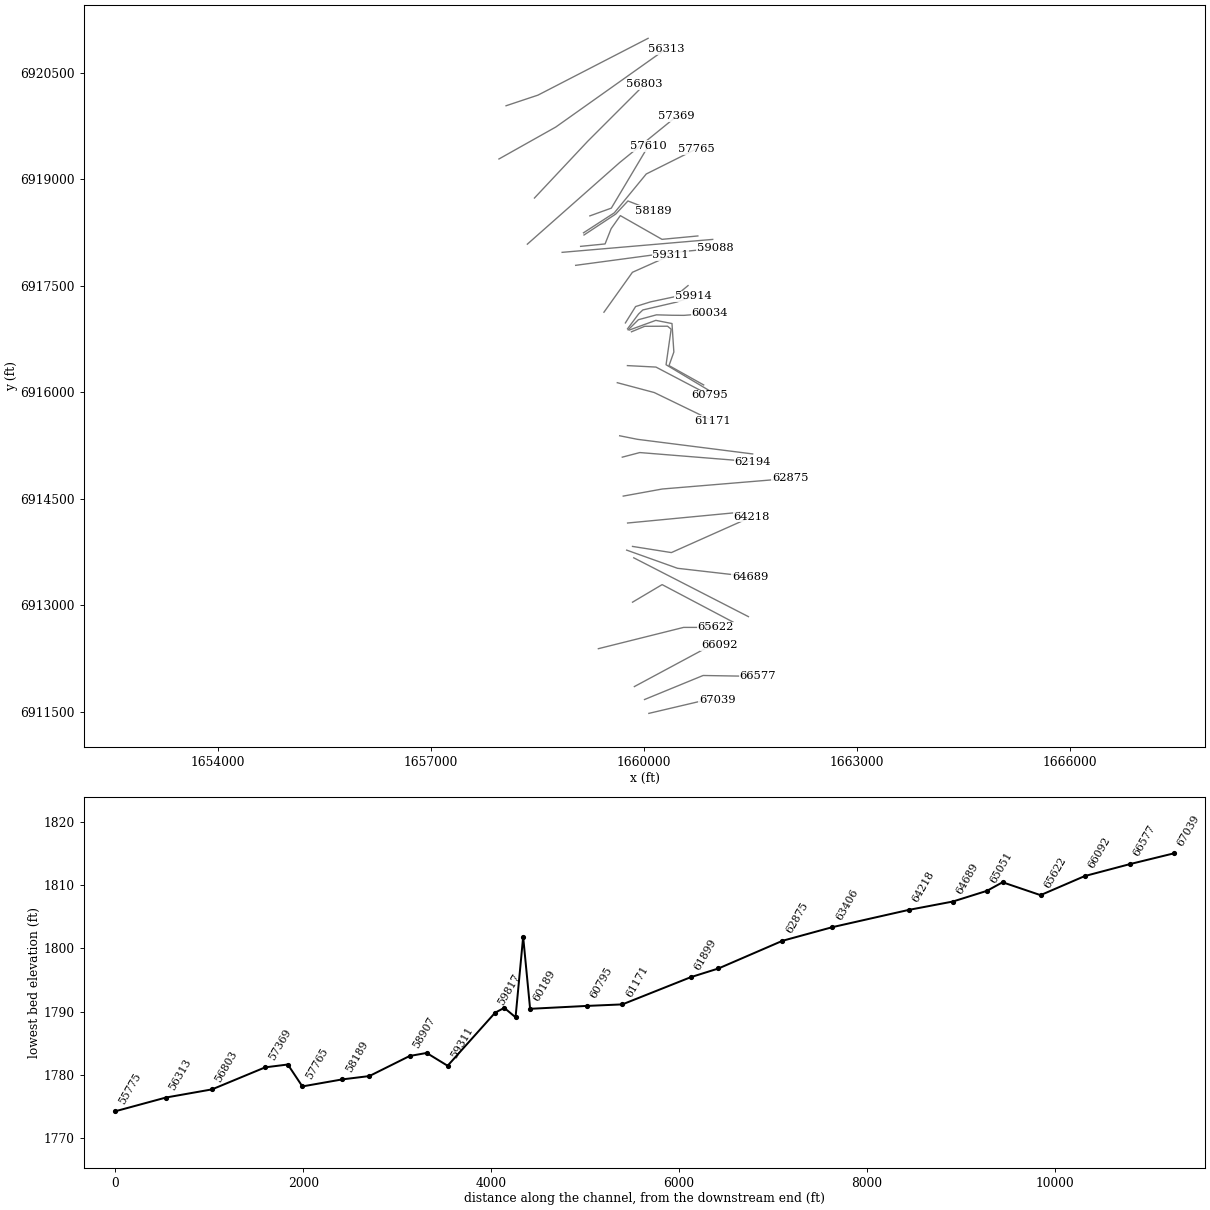
HEC-RAS study Long Creek.prj: Long Creek Base Level Engineering

--- Long Creek.g01 (geometry) --- (continued)

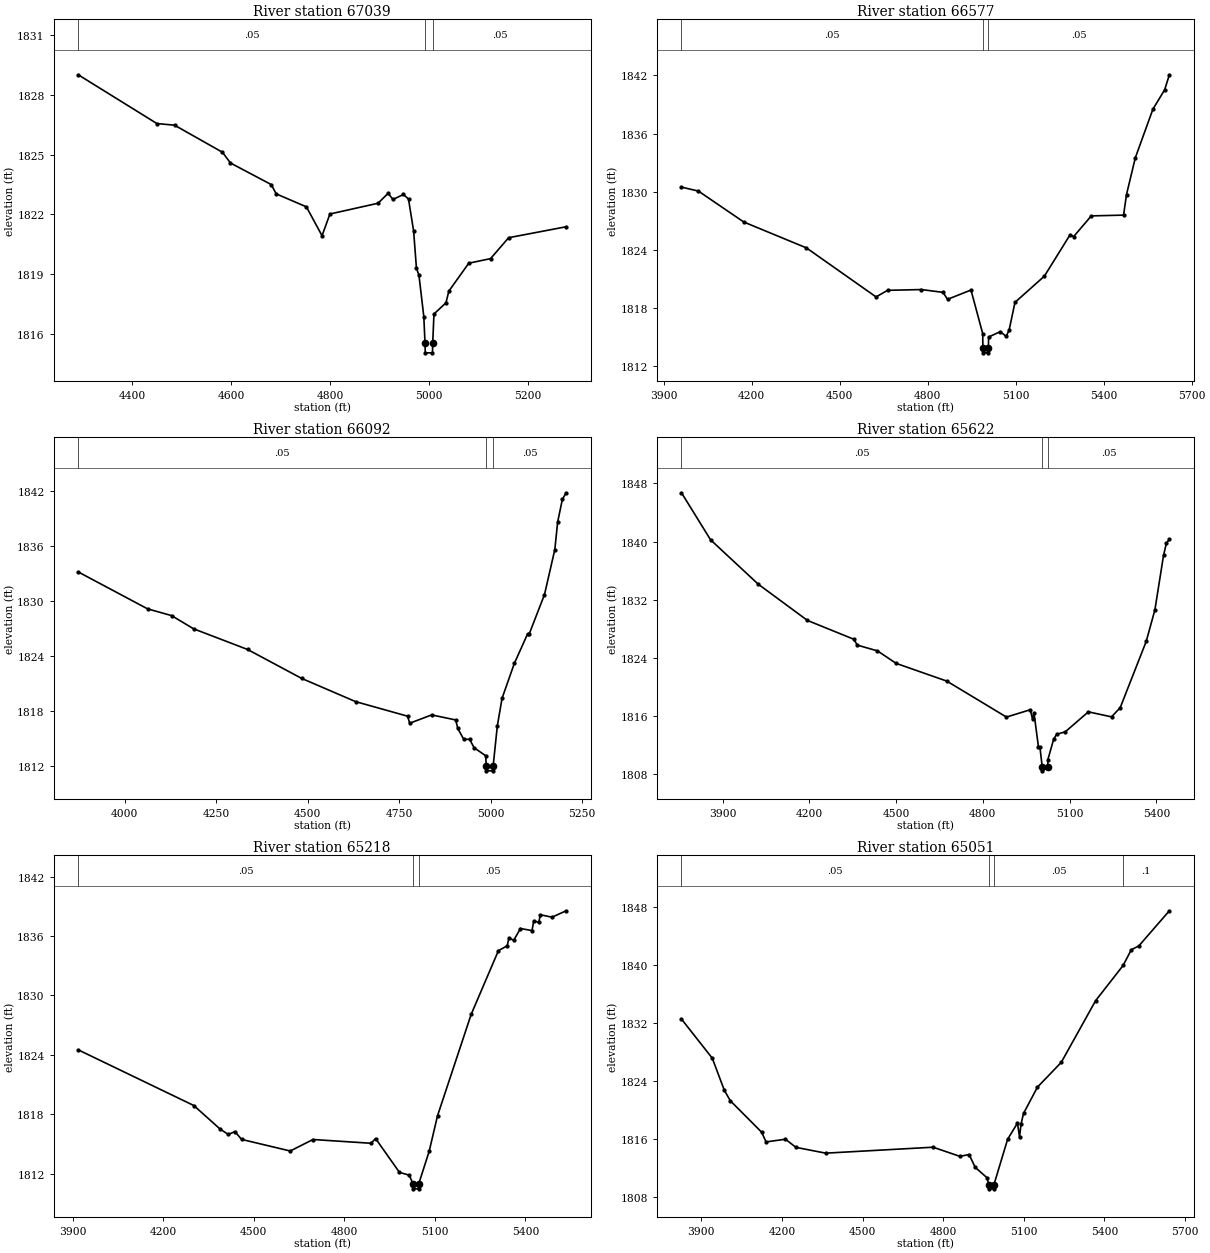
Type RM Length L Ch R = 1,67039,462,462,462
BEGIN DESCRIPTION:
Long Creek 110.0
END DESCRIPTION:
XS GIS Cut Line= 3
      1660065.79      6911476.49      1660760.18      6911639.85
      1661030.34      6911670.14
#Sta/Elev= 30
  4291.4 1829.01  4450.3 1826.56  4485.8 1826.48  4582.6 1825.12  4598.8 1824.58
  4681.0 1823.50  4691.2 1823.03  4752.1 1822.38  4783.7 1820.93  4799.6 1822.02
  4896.7 1822.56  4917.2 1823.06  4926.8 1822.75  4948.1 1823.00  4958.3 1822.77
  4968.6 1821.17  4974.3 1819.31  4979.4 1818.94  4989.2 1816.87  4991.6 1815.55
  4992.1 1815.05  5006.7 1815.05  5007.2 1815.55  5009.7 1817.00  5033.9 1817.56
  5039.8 1818.15  5080.0 1819.55  5124.0 1819.78  5160.5 1820.83  5276.6 1821.38
#Mann=3,-1,0
  4291.4    0.05       0  4991.6    0.05       0  5007.2    0.05       0
Bank Sta=4991.6,5007.2
Exp/Cntr=0.3,0.1

Type RM Length L Ch R = 1,66577,485,485,485
BEGIN DESCRIPTION:
Mapping XS 41c04705
END DESCRIPTION:
XS GIS Cut Line= 3
      1660004.98      6911671.78      1660829.67      6912010.34
      1661601.08      6911997.34
#Sta/Elev= 30
  3961.0 1830.47  4018.7 1830.06  4173.3 1826.87  4386.8 1824.20  4624.2 1819.14
  4663.7 1819.82  4778.8 1819.90  4852.5 1819.61  4867.8 1818.89  4947.8 1819.85
  4987.8 1815.35  4988.4 1813.87  4988.9 1813.37  5006.7 1813.37  5007.2 1813.87
  5007.8 1815.00  5047.8 1815.56  5067.8 1815.06  5077.8 1815.72  5097.8 1818.58
  5197.9 1821.28  5285.4 1825.54  5297.9 1825.37  5357.9 1827.50  5467.9 1827.58
  5477.9 1829.70  5507.9 1833.49  5567.9 1838.51  5607.9 1840.51  5624.0 1842.06
#Mann=3,-1,0
  3961.0    0.05       0  4988.4    0.05       0  5007.2    0.05       0
Bank Sta=4988.4,5007.2
Exp/Cntr=0.3,0.1

Type RM Length L Ch R = 1,66092,470,470,470
BEGIN DESCRIPTION:
Long Creek 109.0
END DESCRIPTION:
XS GIS Cut Line= 3
      1659861.75      6911854.06      1660855.00      6912388.00
      1661054.98      6912437.99
#Sta/Elev= 30
  3872.8 1833.19  4062.2 1829.16  4128.0 1828.42  4188.0 1826.98  4335.7 1824.72
  4483.5 1821.56  4631.2 1819.02  4773.2 1817.43  4778.9 1816.66  4839.0 1817.57
  4904.7 1817.02  4910.4 1816.09  4926.6 1814.91  4942.8 1814.90  4955.1 1813.98
  4986.7 1813.11  4988.2 1811.96  4988.7 1811.46  5006.5 1811.46  5007.0 1811.96
  5018.5 1816.37  5031.4 1819.38  5064.9 1823.19  5101.0 1826.40  5106.1 1826.46
  5147.4 1830.71  5175.7 1835.64  5183.4 1838.64  5196.3 1841.12  5206.6 1841.84
#Mann=3,-1,0
  3872.8    0.05       0  4988.2    0.05       0  5007.0    0.05       0
Bank Sta=4988.2,5007
Exp/Cntr=0.3,0.1

Type RM Length L Ch R = 1,65622,404,404,404
BEGIN DESCRIPTION:
Long Creek 108.0
END DESCRIPTION:
XS GIS Cut Line= 3
      1659354.99      6912388.00      1660555.00      6912688.00
      1661004.96      6912688.00
#Sta/Elev= 30
  3758.1 1846.71  3858.6 1840.24  4023.5 1834.13  4193.6 1829.14  4353.4 1826.56
  4366.3 1825.74  4435.8 1824.95  4500.3 1823.23  4675.5 1820.79  4881.7 1815.84
  4964.1 1816.85  4971.8 1815.57  4977.0 1816.38  4992.5 1811.69  4997.5 1811.69
  5005.5 1808.94  5006.0 1808.44  5024.5 1808.94  5025.0 1809.99  5045.0 1812.80
  5055.0 1813.47  5085.0 1813.81  5165.0 1816.56  5245.0 1815.87  5275.0 1817.13
  5365.0 1826.26  5395.0 1830.60  5425.0 1838.13  5435.0 1839.80  5445.0 1840.28
#Mann=3,-1,0
  3758.1    0.05       0  5005.5    0.03       0  5024.5    0.05       0
Bank Sta=5005.5,5024.5
Exp/Cntr=0.3,0.1

Type RM Length L Ch R = 1,65218,167,167,167
BEGIN DESCRIPTION:
Mapping XS 02e9a9a9
END DESCRIPTION:
XS GIS Cut Line= 3
      1659835.75      6913043.32      1660252.42      6913290.72
      1661253.32      6912762.11
#Sta/Elev= 30
  3918.5 1824.51  4301.4 1818.89  4388.3 1816.52  4415.6 1815.97  4437.7 1816.26
  4459.7 1815.47  4620.9 1814.30  4696.2 1815.46  4888.7 1815.08  4903.6 1815.56
  4982.8 1812.14  5015.1 1811.86  5027.6 1810.98  5028.1 1810.48  5046.1 1810.48
  5046.6 1810.98  5081.2 1814.27  5108.8 1817.85  5220.2 1828.08  5310.7 1834.53
  5339.7 1835.01  5345.3 1835.77  5361.7 1835.59  5383.7 1836.76  5422.1 1836.55
  5427.7 1837.55  5444.1 1837.37  5449.8 1838.15  5488.1 1837.90  5535.0 1838.55
#Mann=3,-1,0
  3918.5    0.05       0  5027.6    0.03       0  5046.6    0.05       0
Bank Sta=5027.6,5046.6
Exp/Cntr=0.3,0.1

Type RM Length L Ch R = 1,65051,362,362,362
BEGIN DESCRIPTION:
Mapping XS 3659b328
END DESCRIPTION:
XS GIS Cut Line= 2
      1659853.08      6913668.34      1661467.69      6912839.33
#Sta/Elev= 30
  3826.5 1832.53  3941.1 1827.13  3985.9 1822.71  4008.1 1821.27  4124.7 1816.93
  4141.2 1815.59  4213.4 1815.96  4252.2 1814.84  4363.1 1814.04  4762.5 1814.86
  4862.2 1813.60  4896.6 1813.85  4919.0 1812.09  4964.0 1810.62  4969.3 1809.62
  4969.8 1809.12  4987.8 1809.12  4988.3 1809.62  5039.7 1815.95  5076.4 1818.18
  5084.1 1816.28  5089.7 1818.05  5098.9 1819.51  5150.7 1823.14  5239.4 1826.56
  5366.9 1835.05  5469.4 1839.92  5500.0 1842.09  5527.8 1842.61  5641.5 1847.46
#Mann=4,-1,0
  3826.5    0.05       0  4969.3    0.05       0  4988.3    0.05       0
  5469.4     0.1       0
Bank Sta=4969.3,4988.3
Exp/Cntr=0.3,0.1

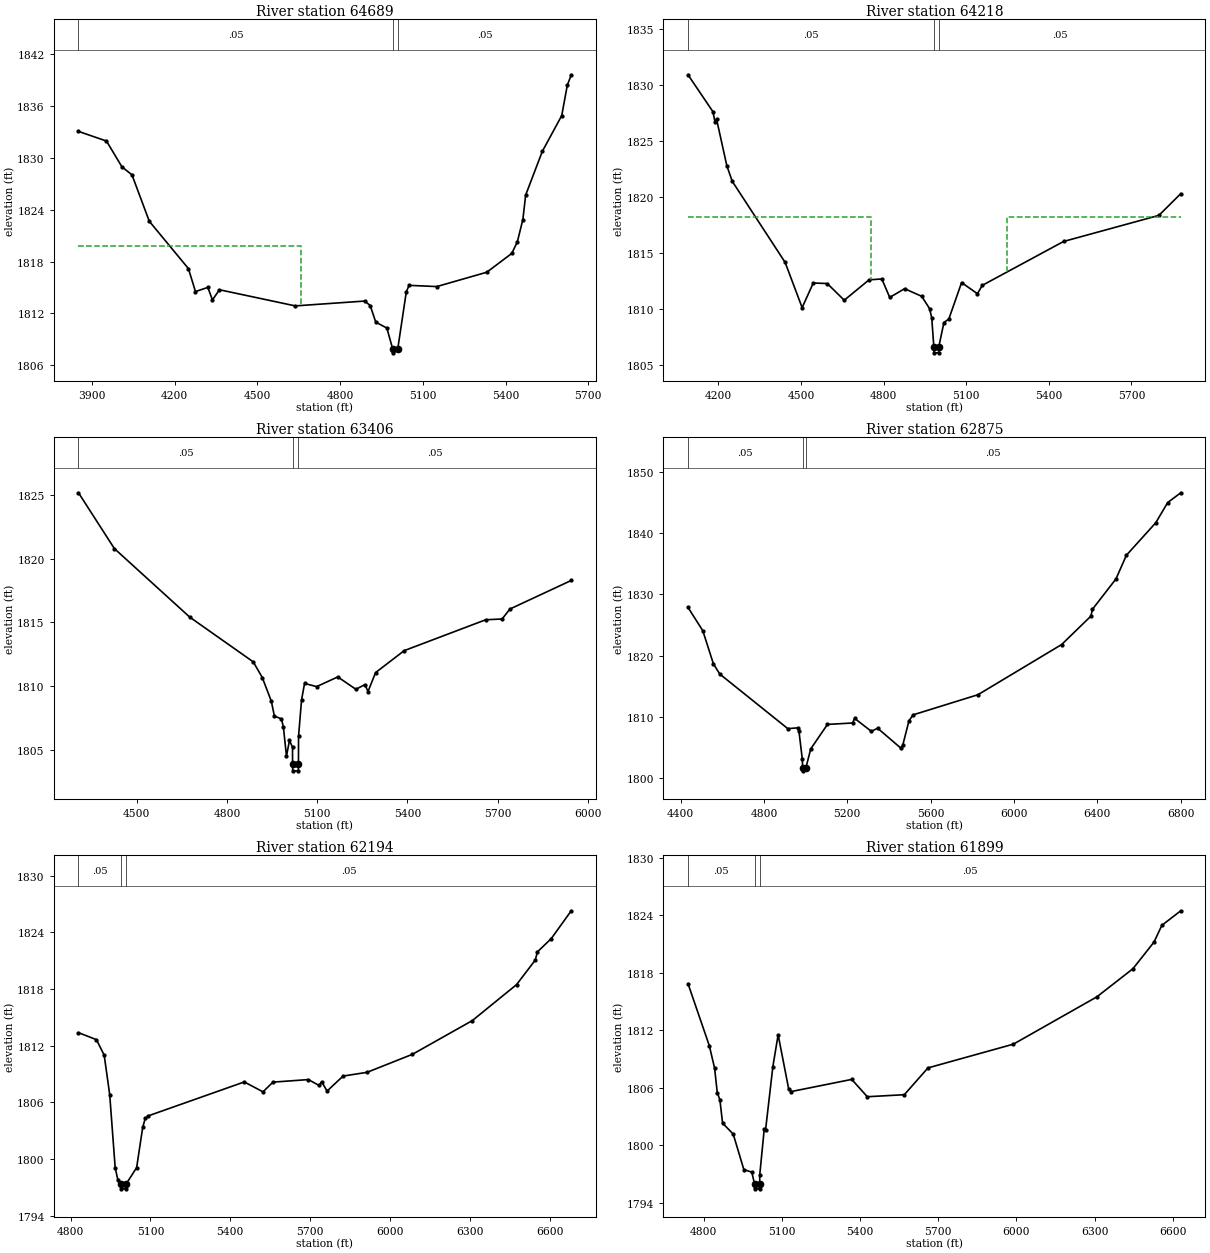
Type RM Length L Ch R = 1,64689,471,471,471
BEGIN DESCRIPTION:
Mapping XS 56528d92
END DESCRIPTION:
XS GIS Cut Line= 3
      1659753.33      6913776.82      1660469.43      6913520.75
      1661489.42      6913403.57
#Sta/Elev= 30
  3851.3 1833.09  3952.8 1831.97  4009.1 1828.97  4045.2 1828.06  4108.0 1822.68
  4250.0 1817.19  4275.5 1814.53  4320.4 1815.01  4337.1 1813.56  4362.5 1814.74
  4637.5 1812.87  4889.2 1813.43  4909.3 1812.91  4929.4 1810.99  4969.7 1810.30
  4990.4 1807.93  4990.9 1807.43  5009.4 1807.93  5040.2 1814.50  5050.2 1815.25
  5150.9 1815.11  5332.1 1816.77  5422.7 1818.95  5442.8 1820.28  5462.9 1822.87
  5473.1 1825.71  5533.4 1830.77  5603.9 1834.92  5624.0 1838.42  5638.5 1839.65
#Mann=3,-1,0
  3851.3    0.05       0  4990.4    0.03       0  5009.4    0.05       0
#XS Ineff=2,0
    0.00 4656.70 1819.80               0
Permanent Ineff=
       F       F
Bank Sta=4990.4,5009.4
Exp/Cntr=0.3,0.1

Type RM Length L Ch R = 1,64218,812,812,812
BEGIN DESCRIPTION:
Mapping XS 4f44d4f1
END DESCRIPTION:
XS GIS Cut Line= 3
      1659835.79      6913828.91      1660382.63      6913742.11
      1661510.57      6914245.35
#Sta/Elev= 30
  4090.2 1830.94  4180.5 1827.65  4188.6 1826.69  4193.7 1826.99  4231.2 1822.81
  4250.9 1821.42  4442.8 1814.18  4504.5 1810.14  4545.0 1812.34  4595.7 1812.29
  4657.4 1810.80  4747.4 1812.62  4793.8 1812.70  4822.5 1811.05  4876.4 1811.83
  4938.6 1811.15  4967.3 1810.04  4975.0 1809.21  4982.7 1806.60  4983.2 1806.10
  4999.8 1806.10  5000.3 1806.60  5019.2 1808.81  5037.0 1809.12  5083.4 1812.38
  5140.8 1811.38  5158.6 1812.13  5453.7 1816.05  5799.6 1818.38  5879.0 1820.32
#Mann=3,-1,0
  4090.2    0.05       0  4982.7    0.03       0  5000.3    0.05       0
#XS Ineff=2,0
    0.00 4753.30 1818.24 5246.70    0.00 1818.24
Permanent Ineff=
       F       F
Bank Sta=4982.7,5000.3
Exp/Cntr=0.3,0.1

Type RM Length L Ch R = 1,63406,531,531,531
BEGIN DESCRIPTION:
Mapping XS 8b4583d8
END DESCRIPTION:
XS GIS Cut Line= 2
      1659766.28      6914158.77      1661398.22      6914315.02
#Sta/Elev= 30
  4306.0 1825.16  4425.3 1820.79  4676.4 1815.41  4887.4 1811.91  4917.5 1810.68
  4947.6 1808.82  4957.7 1807.66  4981.3 1807.44  4987.8 1806.78  4997.9 1804.52
  5007.9 1805.75  5018.0 1805.22  5018.2 1803.87  5018.7 1803.37  5037.3 1803.37
  5037.8 1803.87  5038.1 1806.08  5048.1 1808.93  5058.1 1810.22  5098.3 1809.97
  5168.6 1810.73  5228.9 1809.76  5259.1 1810.13  5269.1 1809.58  5294.4 1811.07
  5389.7 1812.79  5660.9 1815.21  5715.2 1815.27  5741.3 1816.05  5945.4 1818.29
#Mann=3,-1,0
  4306.0    0.05       0  5018.2    0.05       0  5037.8    0.05       0
Bank Sta=5018.2,5037.8
Exp/Cntr=0.3,0.1

Type RM Length L Ch R = 1,62875,681,681,681
BEGIN DESCRIPTION:
Long Creek 104.0
END DESCRIPTION:
XS GIS Cut Line= 3
      1659705.01      6914538.00      1660255.00      6914638.00
      1662054.95      6914788.00
#Sta/Elev= 30
  4435.6 1827.85  4506.7 1824.05  4557.6 1818.65  4588.1 1816.99  4914.6 1808.09
  4962.8 1808.22  4967.9 1807.74  4984.4 1803.08  4985.8 1801.71  4986.2 1801.21
  5001.5 1801.71  5024.7 1804.79  5105.0 1808.78  5225.4 1809.01  5235.4 1809.76
  5315.7 1807.65  5345.8 1808.16  5456.2 1804.94  5466.2 1805.37  5496.3 1809.38
  5516.4 1810.34  5827.5 1813.62  6228.9 1821.80  6369.4 1826.43  6376.9 1827.55
  6489.8 1832.50  6539.9 1836.36  6680.4 1841.64  6738.1 1844.95  6800.8 1846.54
#Mann=3,-1,0
  4435.6    0.05       0  4985.8    0.03       0  5001.5    0.05       0
Bank Sta=4985.8,5001.5
Exp/Cntr=0.3,0.1

Type RM Length L Ch R = 1,62194,295,295,295
BEGIN DESCRIPTION:
Mapping XS d4ac7b0f
END DESCRIPTION:
XS GIS Cut Line= 3
      1659691.59      6915086.69      1659938.30      6915151.51
      1661529.73      6915022.98
#Sta/Elev= 30
  4829.8 1813.38  4897.3 1812.64  4926.4 1810.99  4947.1 1806.81  4967.6 1799.09
  4978.1 1797.72  4988.9 1797.33  4989.4 1796.83  5008.1 1796.83  5008.6 1797.33
  5048.3 1799.08  5071.1 1803.35  5080.6 1804.29  5091.6 1804.56  5452.8 1808.16
  5523.0 1807.11  5560.7 1808.14  5693.6 1808.41  5733.7 1807.79  5743.7 1808.18
  5763.8 1807.19  5824.0 1808.78  5914.3 1809.18  6084.8 1811.09  6309.6 1814.66
  6476.1 1818.48  6546.3 1821.08  6554.2 1821.94  6606.5 1823.36  6681.5 1826.30
#Mann=3,-1,0
  4829.8    0.05       0  4988.9    0.03       0  5008.6    0.05       0
Bank Sta=4988.9,5008.6
Exp/Cntr=0.3,0.1

Type RM Length L Ch R = 1,61899,728,728,728
BEGIN DESCRIPTION:
Long Creek 102.0
END DESCRIPTION:
XS GIS Cut Line= 3
      1659654.96      6915388.01      1659905.00      6915338.00
      1661526.90      6915132.17
#Sta/Elev= 30
  4740.2 1816.88  4821.8 1810.41  4842.2 1808.06  4852.4 1805.51  4862.6 1804.73
  4872.8 1802.31  4913.6 1801.17  4954.4 1797.46  4985.0 1797.19  4995.4 1795.95
  4995.9 1795.45  5014.7 1795.45  5015.2 1795.95  5015.3 1796.89  5032.7 1801.72
  5037.7 1801.61  5065.7 1808.22  5085.9 1811.54  5126.2 1805.90  5136.3 1805.61
  5368.2 1806.88  5427.8 1805.07  5569.8 1805.28  5660.5 1808.08  5988.1 1810.56
  6308.2 1815.50  6446.7 1818.44  6527.4 1821.22  6557.6 1822.97  6630.1 1824.49
#Mann=3,-1,0
  4740.2    0.05       0  4995.4    0.05       0  5015.2    0.05       0
Bank Sta=4995.4,5015.2
Exp/Cntr=0.3,0.1

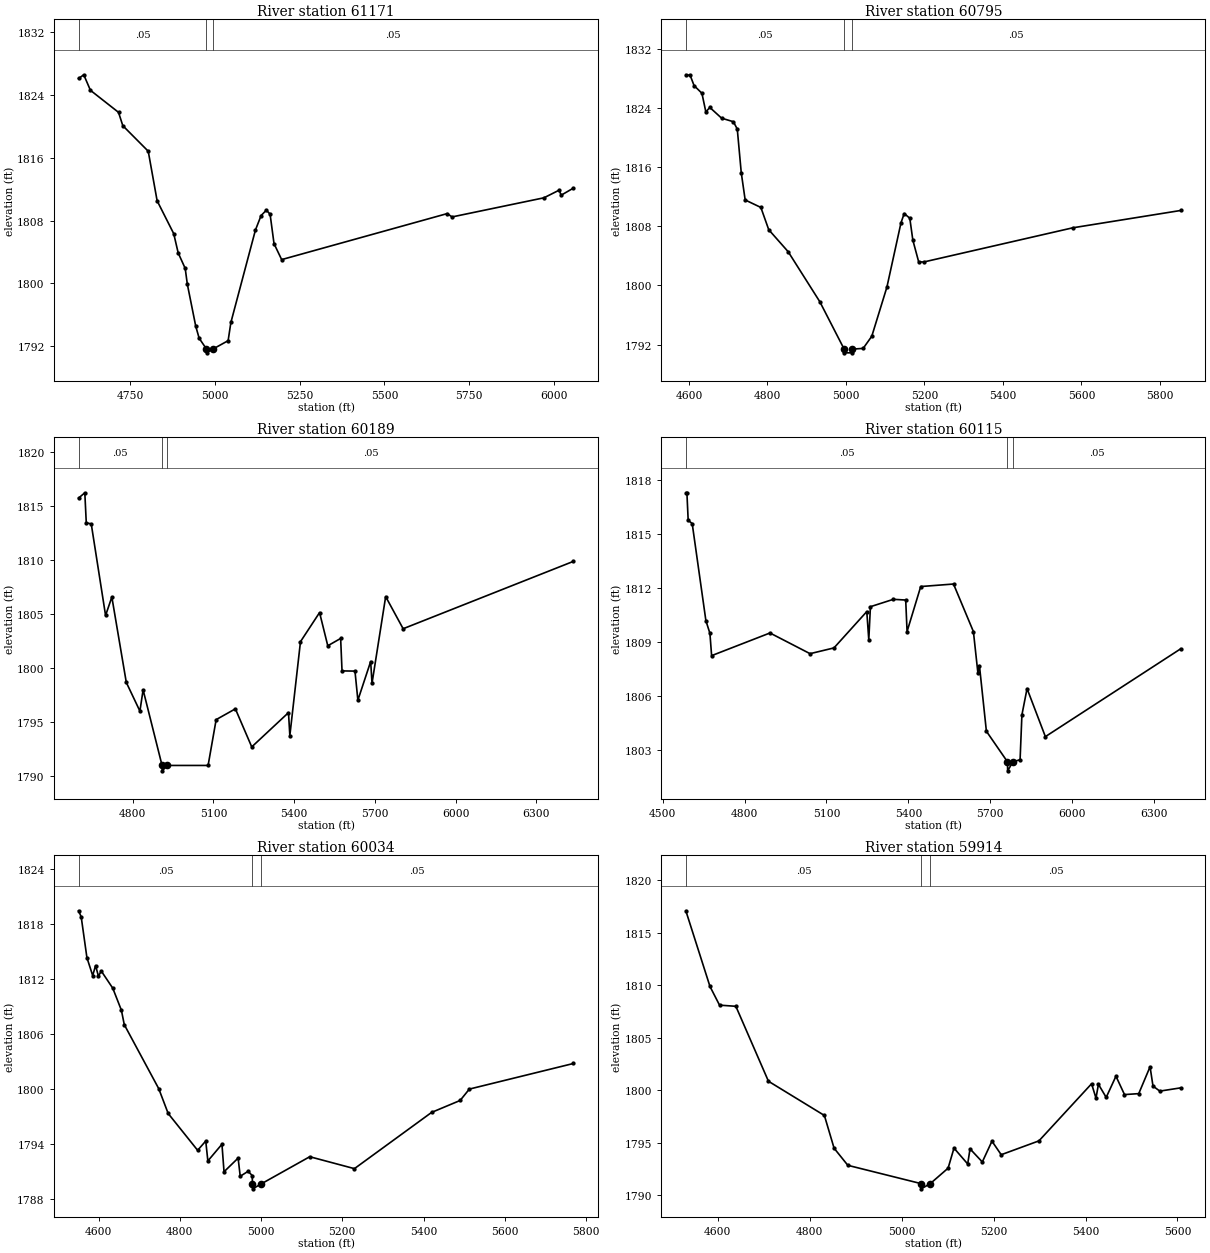
Type RM Length L Ch R = 1,61171,376,376,376
BEGIN DESCRIPTION:
Mapping XS dbdb9eee
END DESCRIPTION:
XS GIS Cut Line= 3
      1659621.28      6916135.82      1660142.15      6915996.93
      1660969.64      6915595.70
#Sta/Elev= 30
  4598.4 1826.13  4613.6 1826.60  4633.3 1824.62  4716.1 1821.81  4728.7 1820.11
  4803.7 1816.85  4829.9 1810.53  4878.8 1806.34  4892.0 1803.88  4912.7 1801.90
  4918.9 1799.90  4943.8 1794.52  4953.8 1793.00  4975.2 1791.64  4975.7 1791.14
  4995.1 1791.64  5039.2 1792.69  5047.3 1795.01  5119.7 1806.80  5136.4 1808.65
  5151.9 1809.33  5162.9 1808.82  5174.5 1805.06  5197.0 1803.03  5685.2 1808.90
  5699.2 1808.47  5970.1 1810.91  6015.2 1811.89  6020.8 1811.24  6057.1 1812.15
#Mann=3,-1,0
  4598.4    0.05       0  4975.2    0.05       0  4995.1    0.05       0
Bank Sta=4975.2,4995.1
Exp/Cntr=0.3,0.1

Type RM Length L Ch R = 1,60795,606,606,606
BEGIN DESCRIPTION:
Long Creek 100.0
END DESCRIPTION:
XS GIS Cut Line= 3
      1659764.03      6916376.69      1660165.67      6916355.94
      1660926.12      6915956.62
#Sta/Elev= 30
  4591.9 1828.46  4602.9 1828.39  4612.9 1827.00  4632.9 1825.96  4642.9 1823.44
  4653.0 1824.05  4683.0 1822.60  4713.0 1822.12  4723.0 1821.13  4733.1 1815.25
  4743.1 1811.55  4783.1 1810.54  4803.2 1807.53  4852.7 1804.56  4933.3 1797.81
  4995.4 1791.40  4995.9 1790.90  5014.8 1790.90  5015.3 1791.40  5043.8 1791.50
  5065.8 1793.14  5104.3 1799.77  5140.2 1808.46  5148.4 1809.72  5162.7 1809.08
  5170.4 1806.13  5185.3 1803.19  5198.1 1803.17  5578.1 1807.79  5853.0 1810.13
#Mann=3,-1,0
  4591.9    0.05       0  4995.4    0.05       0  5015.3    0.05       0
Bank Sta=4995.4,5015.3
Exp/Cntr=0.3,0.1

Type RM Length L Ch R = 1,60189,74,74,74
BEGIN DESCRIPTION:
Long Creek 99.0
END DESCRIPTION:
XS GIS Cut Line= 6
      1659820.90      6916853.23      1660007.08      6916930.38
      1660328.89      6916931.72      1660379.49      6916890.12
      1660308.03      6916388.93      1660943.48      6916008.70
#Sta/Elev= 30
  4599.3 1815.74  4622.4 1816.23  4627.8 1813.45  4646.3 1813.34  4699.5 1804.85
  4722.8 1806.56  4776.5 1798.64  4827.0 1795.98  4838.9 1797.95  4909.3 1790.94
  4909.8 1790.44  4929.2 1790.94  5080.3 1790.94  5110.2 1795.19  5181.6 1796.19
  5242.4 1792.66  5378.9 1795.84  5383.9 1793.71  5423.4 1802.42  5494.3 1805.12
  5524.8 1802.04  5572.6 1802.72  5577.7 1799.71  5625.8 1799.69  5636.6 1796.99
  5684.1 1800.58  5689.1 1798.56  5739.8 1806.60  5804.7 1803.62  6437.2 1809.87
#Mann=3,-1,0
  4599.3    0.05       0  4909.3    0.05       0  4929.2    0.05       0
Bank Sta=4909.3,4929.2
Exp/Cntr=0.3,0.1

Type RM Length L Ch R = 1,60115,81,81,81
BEGIN DESCRIPTION:
Mapping XS b602a746
END DESCRIPTION:
XS GIS Cut Line= 6
      1659792.39      6916878.41      1660163.81      6917014.16
      1660391.41      6916969.24      1660417.65      6916567.93
      1660349.69      6916376.78      1660837.54      6916104.21
#Sta/Elev= 30
  4585.0 1817.29  4588.9 1817.29  4593.6 1815.76  4608.3 1815.58  4658.5 1810.18
  4673.2 1809.48  4679.4 1808.24  4893.1 1809.50  5039.9 1808.35  5127.5 1808.67
  5247.7 1810.69  5255.0 1809.12  5261.0 1810.96  5345.1 1811.37  5390.2 1811.33
  5395.2 1809.58  5445.2 1812.08  5565.3 1812.22  5638.1 1809.58  5654.8 1807.25
  5660.2 1807.69  5685.7 1804.04  5763.0 1802.34  5763.5 1801.84  5782.9 1802.34
  5809.1 1802.46  5815.8 1804.95  5834.6 1806.41  5901.7 1803.74  6397.2 1808.62
#Mann=3,-1,0
  4585.0    0.05       0  5763.0    0.03       0  5782.9    0.05       0
Bank Sta=5763,5782.9
Exp/Cntr=0.3,0.1

Type RM Length L Ch R = 1,60034,120,120,120
BEGIN DESCRIPTION:
Mapping XS 3404a1ed
END DESCRIPTION:
XS GIS Cut Line= 6
      1659773.91      6916880.07      1659918.24      6917023.14
      1660172.79      6917092.02      1660391.41      6917086.03
      1660558.99      6917084.71      1660923.17      6917113.11
#Sta/Elev= 30
  4550.7 1819.40  4557.1 1818.74  4571.2 1814.29  4585.4 1812.34  4592.5 1813.43
  4599.5 1812.28  4606.6 1812.83  4634.9 1810.96  4656.1 1808.56  4663.2 1806.99
  4748.0 1800.02  4771.3 1797.31  4843.8 1793.30  4863.8 1794.31  4869.0 1792.14
  4903.7 1793.96  4908.8 1790.96  4943.5 1792.45  4948.7 1790.47  4968.1 1791.01
  4978.2 1790.55  4978.9 1789.60  4979.4 1789.10  4998.8 1789.60  5119.9 1792.60
  5229.9 1791.30  5420.0 1797.43  5490.2 1798.73  5512.9 1799.97  5769.2 1802.76
#Mann=3,-1,0
  4550.7    0.05       0  4978.9    0.05       0  4998.8    0.05       0
Bank Sta=4978.9,4998.8
Exp/Cntr=0.3,0.1

Type RM Length L Ch R = 1,59914,97,97,97
BEGIN DESCRIPTION:
Mapping XS f8bd76d8
END DESCRIPTION:
XS GIS Cut Line= 5
      1659765.49      6916895.12      1659921.24      6917104.00
      1659981.13      6917160.90      1660457.29      6917271.70
      1660687.88      6917352.56
#Sta/Elev= 30
  4530.6 1817.08  4583.1 1809.87  4603.9 1808.09  4639.4 1807.98  4710.3 1800.84
  4832.0 1797.58  4853.1 1794.46  4883.0 1792.83  5042.1 1791.09  5042.6 1790.59
  5062.4 1791.09  5101.1 1792.56  5113.9 1794.47  5143.7 1792.96  5148.8 1794.40
  5175.5 1793.15  5196.5 1795.13  5216.6 1793.84  5298.7 1795.16  5413.2 1800.60
  5422.8 1799.23  5428.1 1800.55  5445.0 1799.30  5466.2 1801.32  5484.8 1799.57
  5515.8 1799.66  5540.4 1802.22  5546.8 1800.38  5561.6 1799.90  5607.0 1800.21
#Mann=3,-1,0
  4530.6    0.05       0  5042.1    0.03       0  5062.4    0.05       0
Bank Sta=5042.1,5062.4
Exp/Cntr=0.3,0.1

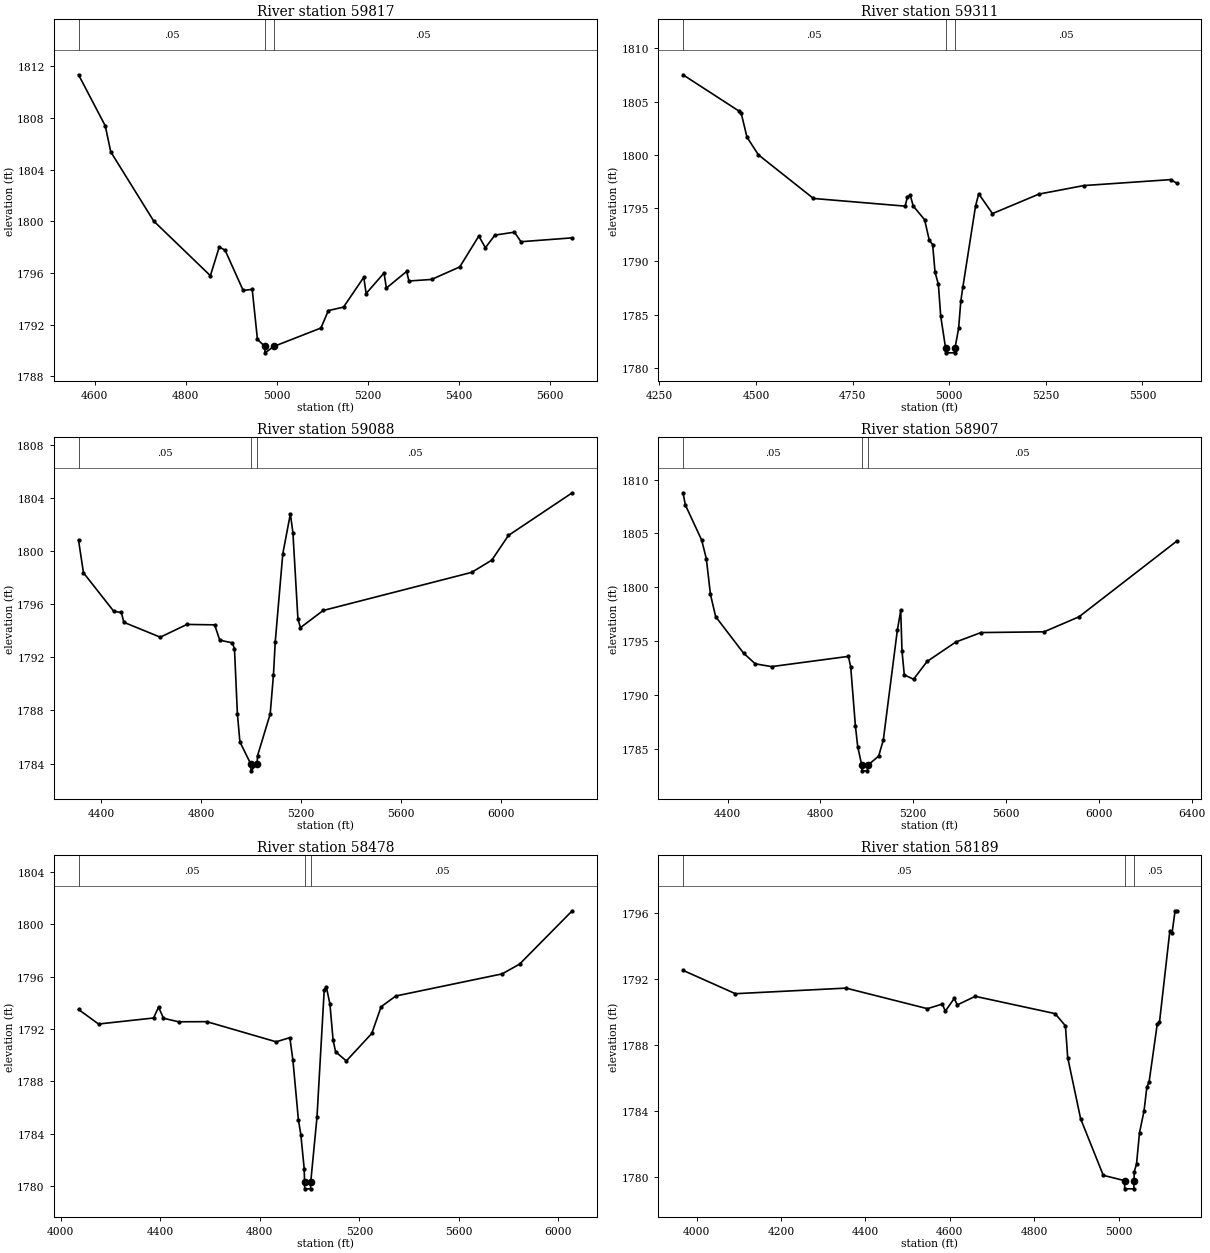
Type RM Length L Ch R = 1,59817,506,506,506
BEGIN DESCRIPTION:
Mapping XS 898a6e31
END DESCRIPTION:
XS GIS Cut Line= 5
      1659735.56      6916978.21      1659879.31      6917208.82
      1660088.94      6917274.70      1660427.34      6917346.57
      1660617.64      6917504.16
#Sta/Elev= 30
  4564.5 1811.35  4623.2 1807.40  4635.2 1805.39  4729.6 1800.03  4854.1 1795.80
  4873.6 1798.02  4886.5 1797.77  4926.1 1794.66  4946.0 1794.74  4957.5 1790.87
  4973.5 1790.33  4974.0 1789.83  4993.8 1790.33  5096.9 1791.75  5113.3 1793.10
  5146.6 1793.37  5191.1 1795.68  5196.2 1794.42  5235.6 1796.01  5240.7 1794.84
  5285.2 1796.13  5290.3 1795.39  5340.0 1795.51  5401.9 1796.48  5443.8 1798.87
  5458.2 1797.96  5479.0 1798.94  5522.0 1799.17  5536.3 1798.43  5649.0 1798.73
#Mann=3,-1,0
  4564.5    0.05       0  4973.5    0.03       0  4993.8    0.05       0
Bank Sta=4973.5,4993.8
Exp/Cntr=0.3,0.1

Type RM Length L Ch R = 1,59311,223,223,223
BEGIN DESCRIPTION:
Mapping XS b6ec2a31
END DESCRIPTION:
XS GIS Cut Line= 3
      1659433.38      6917128.87      1659834.42      6917691.37
      1660370.47      6917930.77
#Sta/Elev= 30
  4310.9 1807.52  4455.6 1804.12  4461.7 1803.89  4476.5 1801.67  4506.0 1800.01
  4648.6 1795.91  4885.8 1795.19  4892.0 1796.07  4899.3 1796.21  4906.7 1795.21
  4936.2 1793.92  4948.5 1791.98  4957.1 1791.58  4963.3 1788.99  4971.9 1787.86
  4978.0 1784.86  4990.4 1781.92  4990.9 1781.42  5014.7 1781.42  5015.2 1781.92
  5024.3 1783.71  5030.0 1786.28  5035.5 1787.64  5068.1 1795.19  5076.4 1796.35
  5111.9 1794.49  5232.3 1796.32  5348.2 1797.12  5573.5 1797.68  5588.8 1797.34
#Mann=3,-1,0
  4310.9    0.05       0  4990.4    0.03       0  5015.2    0.05       0
Bank Sta=4990.4,5015.2
Exp/Cntr=0.3,0.1

Type RM Length L Ch R = 1,59088,181,181,181
BEGIN DESCRIPTION:
Mapping XS 403b7724
END DESCRIPTION:
XS GIS Cut Line= 3
      1659035.44      6917789.53      1660282.34      6917957.00
      1660995.09      6918028.25
#Sta/Elev= 30
  4310.5 1800.81  4330.2 1798.36  4451.3 1795.46  4481.6 1795.37  4491.8 1794.63
  4637.5 1793.51  4743.9 1794.47  4854.9 1794.44  4875.1 1793.29  4925.5 1793.08
  4934.1 1792.65  4945.7 1787.76  4955.8 1785.63  4999.6 1783.95  5000.1 1783.45
  5024.4 1783.95  5026.4 1784.59  5076.9 1787.73  5089.9 1790.64  5097.1 1793.15
  5127.3 1799.78  5157.6 1802.79  5167.8 1801.38  5187.9 1794.86  5198.0 1794.23
  5288.8 1795.52  5882.8 1798.39  5963.2 1799.31  6029.8 1801.17  6284.9 1804.38
#Mann=3,-1,0
  4310.5    0.05       0  4999.6    0.05       0  5024.4    0.05       0
Bank Sta=4999.6,5024.4
Exp/Cntr=0.3,0.1

Type RM Length L Ch R = 1,58907,429,429,429
BEGIN DESCRIPTION:
Mapping XS 7697f69f
END DESCRIPTION:
XS GIS Cut Line= 2
      1658844.81      6917972.62      1660964.59      6918154.91
#Sta/Elev= 30
  4207.7 1808.77  4217.9 1807.64  4288.2 1804.38  4308.3 1802.65  4326.1 1799.34
  4348.4 1797.28  4468.8 1793.89  4519.0 1792.90  4589.3 1792.64  4920.5 1793.59
  4930.5 1792.61  4950.6 1787.16  4960.7 1785.21  4978.4 1783.47  4978.9 1782.97
  5002.7 1782.97  5003.2 1783.47  5051.0 1784.34  5071.1 1785.85  5131.3 1796.00
  5146.1 1797.85  5151.4 1794.12  5161.4 1791.87  5201.5 1791.47  5259.7 1793.12
  5383.3 1794.92  5491.8 1795.80  5763.6 1795.87  5914.2 1797.26  6335.3 1804.28
#Mann=3,-1,0
  4207.7    0.05       0  4978.4    0.03       0  5003.2    0.05       0
Bank Sta=4978.4,5003.2
Exp/Cntr=0.3,0.1

Type RM Length L Ch R = 1,58478,289,289,289
BEGIN DESCRIPTION:
Mapping XS 5d4cdd8c
END DESCRIPTION:
XS GIS Cut Line= 6
      1659104.85      6918056.84      1659449.27      6918090.94
      1659534.53      6918305.80      1659664.13      6918489.97
      1660250.73      6918155.74      1660755.48      6918203.49
#Sta/Elev= 30
  4071.2 1793.49  4151.7 1792.38  4372.8 1792.84  4392.9 1793.67  4412.7 1792.82
  4473.4 1792.55  4586.8 1792.56  4865.8 1791.02  4920.7 1791.34  4933.0 1789.60
  4955.2 1785.03  4964.8 1783.94  4978.2 1781.34  4979.7 1780.29  4980.2 1779.79
  5004.0 1779.79  5004.5 1780.29  5029.6 1785.24  5058.8 1794.98  5067.1 1795.23
  5081.8 1793.90  5094.4 1791.16  5104.5 1790.26  5147.7 1789.56  5250.0 1791.66
  5287.5 1793.70  5346.5 1794.52  5774.1 1796.21  5844.4 1796.96  6055.8 1801.03
#Mann=3,-1,0
  4071.2    0.05       0  4979.7    0.03       0  5004.5    0.05       0
Bank Sta=4979.7,5004.5
Exp/Cntr=0.3,0.1

Type RM Length L Ch R = 1,58189,424,424,424
BEGIN DESCRIPTION:
Mapping XS 882fcac9
END DESCRIPTION:
XS GIS Cut Line= 4
      1659152.61      6918217.03      1659599.69      6918512.19
      1659771.14      6918696.65      1660127.04      6918557.76
#Sta/Elev= 30
  3967.8 1792.54  4092.0 1791.12  4354.0 1791.46  4546.8 1790.21  4582.0 1790.49
  4589.3 1790.06  4610.3 1790.83  4617.7 1790.44  4660.2 1790.96  4849.3 1789.91
  4873.8 1789.17  4879.2 1787.24  4909.8 1783.52  4963.5 1780.08  5013.9 1779.76
  5014.3 1779.26  5035.8 1779.26  5036.3 1779.76  5036.9 1780.31  5042.2 1780.76
  5049.3 1782.67  5060.1 1784.01  5066.7 1785.44  5072.1 1785.77  5091.2 1789.25
  5096.6 1789.38  5121.1 1794.92  5126.4 1794.81  5133.6 1796.16  5137.4 1796.16
#Mann=3,-1,0
  3967.8    0.05       0  5013.9    0.05       0  5036.3    0.05       0
Bank Sta=5013.9,5036.3
Exp/Cntr=0.3,0.1

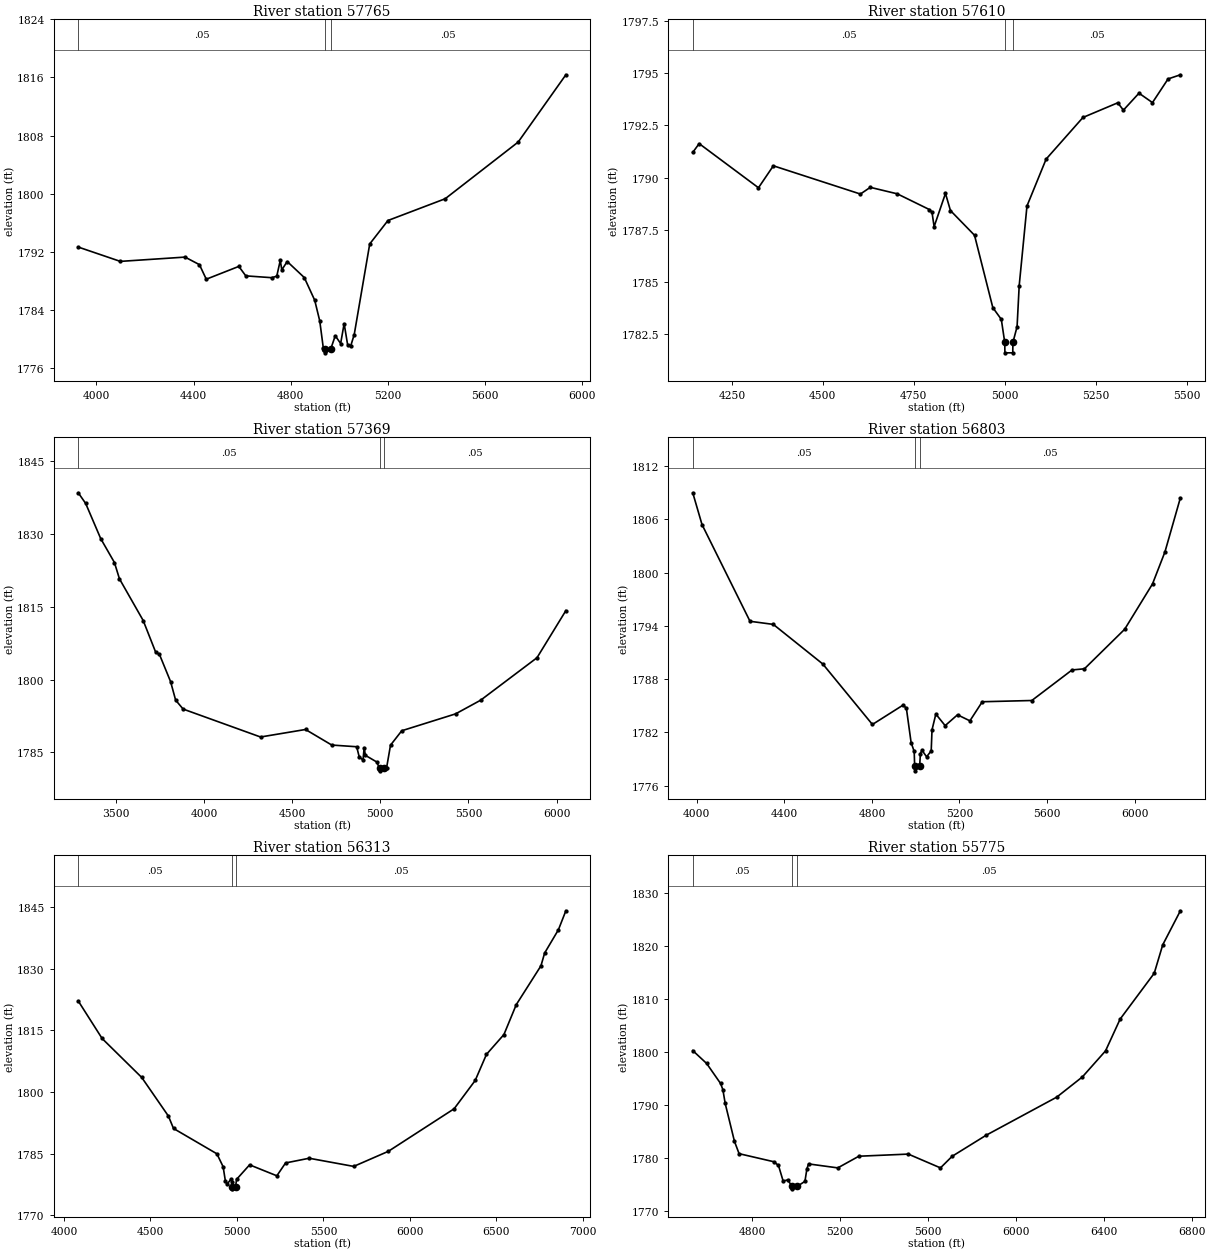
Type RM Length L Ch R = 1,57765,155,155,155
BEGIN DESCRIPTION:
Long Creek 95.0
END DESCRIPTION:
XS GIS Cut Line= 4
      1659145.78      6918247.85      1659579.75      6918529.53
      1660029.05      6919076.57      1660730.84      6919427.46
#Sta/Elev= 30
  3924.9 1792.69  4098.3 1790.72  4365.1 1791.31  4424.5 1790.27  4452.6 1788.27
  4586.8 1790.03  4615.5 1788.73  4722.4 1788.48  4743.2 1788.69  4757.6 1790.85
  4764.0 1789.56  4786.3 1790.70  4856.6 1788.50  4899.6 1785.38  4920.4 1782.53
  4934.8 1778.87  4943.0 1778.65  4943.5 1778.15  4965.4 1778.65  4984.3 1780.50
  5006.5 1779.43  5020.9 1782.17  5035.2 1779.27  5048.5 1779.15  5062.5 1780.67
  5126.4 1793.12  5201.5 1796.34  5437.4 1799.33  5738.2 1807.12  5934.8 1816.37
#Mann=3,-1,0
  3924.9    0.05       0  4943.0    0.03       0  4965.4    0.05       0
Bank Sta=4943,4965.4
Exp/Cntr=0.3,0.1

Type RM Length L Ch R = 1,57610,241,241,241
BEGIN DESCRIPTION:
Mapping XS 7efccafd
END DESCRIPTION:
XS GIS Cut Line= 3
      1659235.30      6918486.35      1659537.35      6918595.71
      1660058.17      6919470.70
#Sta/Elev= 30
  4142.6 1791.20  4160.2 1791.62  4323.1 1789.51  4364.0 1790.56  4603.1 1789.21
  4630.3 1789.53  4704.4 1789.22  4792.4 1788.47  4799.8 1788.34  4805.6 1787.65
  4836.8 1789.24  4850.5 1788.42  4916.6 1787.24  4966.9 1783.78  4990.2 1783.22
  4999.6 1782.12  5000.1 1781.62  5021.6 1781.62  5022.1 1782.12  5033.5 1782.87
  5039.3 1784.83  5060.7 1788.64  5113.3 1790.88  5214.5 1792.87  5310.0 1793.57
  5325.6 1793.22  5368.4 1794.03  5405.4 1793.58  5448.2 1794.71  5482.1 1794.91
#Mann=3,-1,0
  4142.6    0.05       0  4999.6    0.03       0  5022.1    0.05       0
Bank Sta=4999.6,5022.1
Exp/Cntr=0.3,0.1

Type RM Length L Ch R = 1,57369,566,566,566
BEGIN DESCRIPTION:
Long Creek 94.0
END DESCRIPTION:
XS GIS Cut Line= 3
      1658354.99      6918087.99      1659655.00      6919238.00
      1660455.04      6919888.03
#Sta/Elev= 30
  3286.3 1838.53  3328.5 1836.33  3413.9 1829.07  3491.7 1824.14  3520.1 1820.78
  3654.8 1812.18  3725.9 1805.62  3746.8 1805.21  3810.4 1799.56  3838.8 1795.76
  3881.5 1793.91  4320.6 1788.15  4575.7 1789.70  4724.6 1786.49  4866.0 1786.14
  4880.2 1784.08  4901.8 1783.39  4908.6 1785.96  4915.3 1784.37  4979.7 1783.00
  4996.0 1781.67  4996.5 1781.17  5018.6 1781.67  5035.6 1781.77  5057.9 1786.46
  5121.8 1789.44  5427.1 1792.92  5569.3 1795.74  5889.0 1804.50  6052.8 1814.22
#Mann=3,-1,0
  3286.3    0.05       0  4996.0    0.03       0  5018.6    0.05       0
Bank Sta=4996,5018.6
Exp/Cntr=0.3,0.1

Type RM Length L Ch R = 1,56803,490,490,490
BEGIN DESCRIPTION:
Long Creek 93.0
END DESCRIPTION:
XS GIS Cut Line= 3
      1658454.99      6918737.99      1659205.00      6919538.00
      1660005.02      6920338.02
#Sta/Elev= 30
  3981.3 1808.99  4023.6 1805.41  4242.9 1794.52  4349.4 1794.17  4575.5 1789.71
  4802.2 1782.90  4943.3 1785.10  4957.5 1784.70  4979.0 1780.86  4993.1 1779.86
  4995.2 1778.18  4995.7 1777.68  5017.9 1778.18  5021.5 1779.62  5028.3 1780.01
  5049.8 1779.26  5070.8 1779.93  5074.5 1782.30  5092.0 1784.07  5134.5 1782.77
  5191.0 1783.99  5247.6 1783.31  5304.2 1785.46  5530.5 1785.60  5714.3 1789.04
  5770.9 1789.17  5954.7 1793.62  6082.0 1798.73  6138.6 1802.32  6209.3 1808.42
#Mann=3,-1,0
  3981.3    0.05       0  4995.2    0.03       0  5017.9    0.05       0
Bank Sta=4995.2,5017.9
Exp/Cntr=0.3,0.1

Type RM Length L Ch R = 1,56313,538,538,538
BEGIN DESCRIPTION:
Long Creek 92.0
END DESCRIPTION:
XS GIS Cut Line= 3
      1657954.99      6919287.99      1658755.00      6919738.00
      1660305.04      6920838.03
#Sta/Elev= 30
  4082.5 1822.20  4220.5 1813.05  4449.7 1803.54  4603.6 1794.14  4633.2 1791.11
  4884.1 1784.93  4920.1 1781.77  4933.1 1778.27  4943.0 1777.55  4965.0 1778.72
  4970.8 1778.11  4971.8 1776.89  4972.2 1776.39  4992.1 1776.89  4997.5 1778.69
  5073.0 1782.24  5230.5 1779.57  5280.9 1782.70  5417.3 1783.85  5674.8 1781.86
  5875.1 1785.54  6255.2 1795.91  6377.0 1802.81  6442.2 1809.18  6543.1 1814.01
  6614.4 1821.30  6757.1 1830.77  6778.4 1833.89  6858.0 1839.56  6901.1 1844.19
#Mann=3,-1,0
  4082.5    0.05       0  4971.8    0.05       0  4992.1    0.05       0
Bank Sta=4971.8,4992.1
Exp/Cntr=0.3,0.1

Type RM Length L Ch R = 1,55775,591,591,591
BEGIN DESCRIPTION:
Long Creek 91.0
END DESCRIPTION:
XS GIS Cut Line= 3
      1658055.00      6920038.00      1658505.00      6920188.00
      1660054.98      6920987.99
#Sta/Elev= 30
  4530.3 1800.29  4593.5 1797.86  4656.8 1794.09  4667.3 1792.93  4677.9 1790.32
  4720.0 1783.18  4741.1 1780.85  4899.2 1779.33  4920.3 1778.63  4941.4 1775.71
  4962.5 1775.89  4981.5 1774.72  4982.0 1774.22  5006.8 1774.72  5040.7 1775.63
  5049.7 1777.99  5057.2 1778.92  5190.1 1778.17  5286.0 1780.37  5511.0 1780.77
  5657.3 1778.17  5710.6 1780.36  5865.7 1784.34  6186.3 1791.51  6303.2 1795.33
  6408.3 1800.23  6474.8 1806.23  6629.9 1814.87  6668.6 1820.23  6748.9 1826.65
#Mann=3,-1,0
  4530.3    0.05       0  4981.5    0.03       0  5006.8    0.05       0
Bank Sta=4981.5,5006.8
Exp/Cntr=0.3,0.1