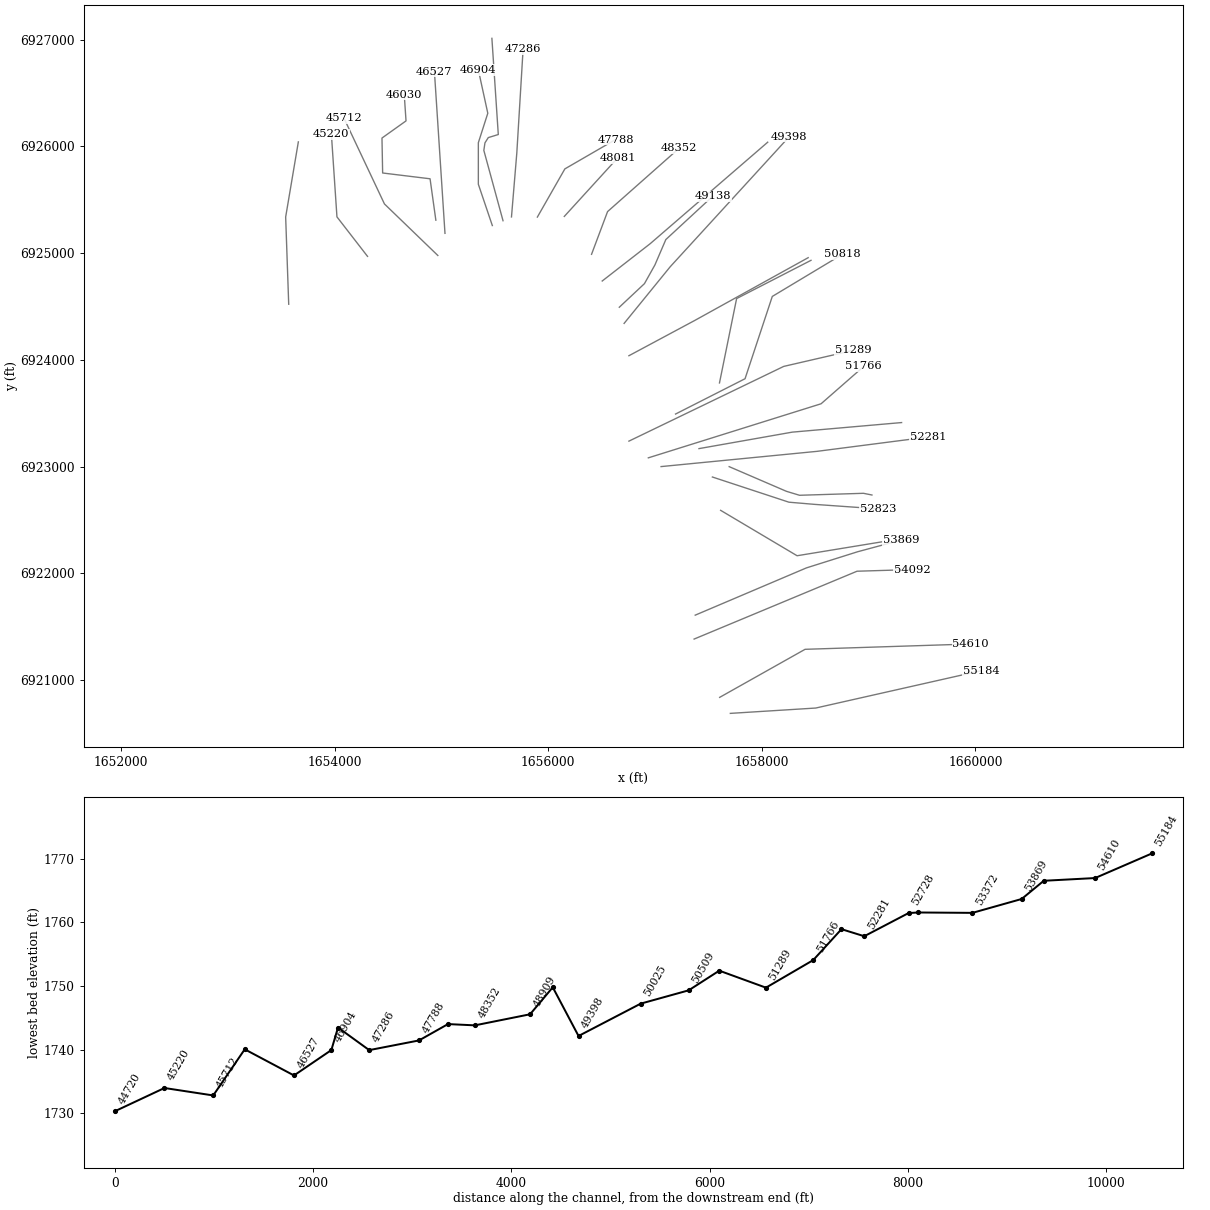
HEC-RAS study Long Creek.prj: Long Creek Base Level Engineering

--- Long Creek.g01 (geometry) --- (continued)

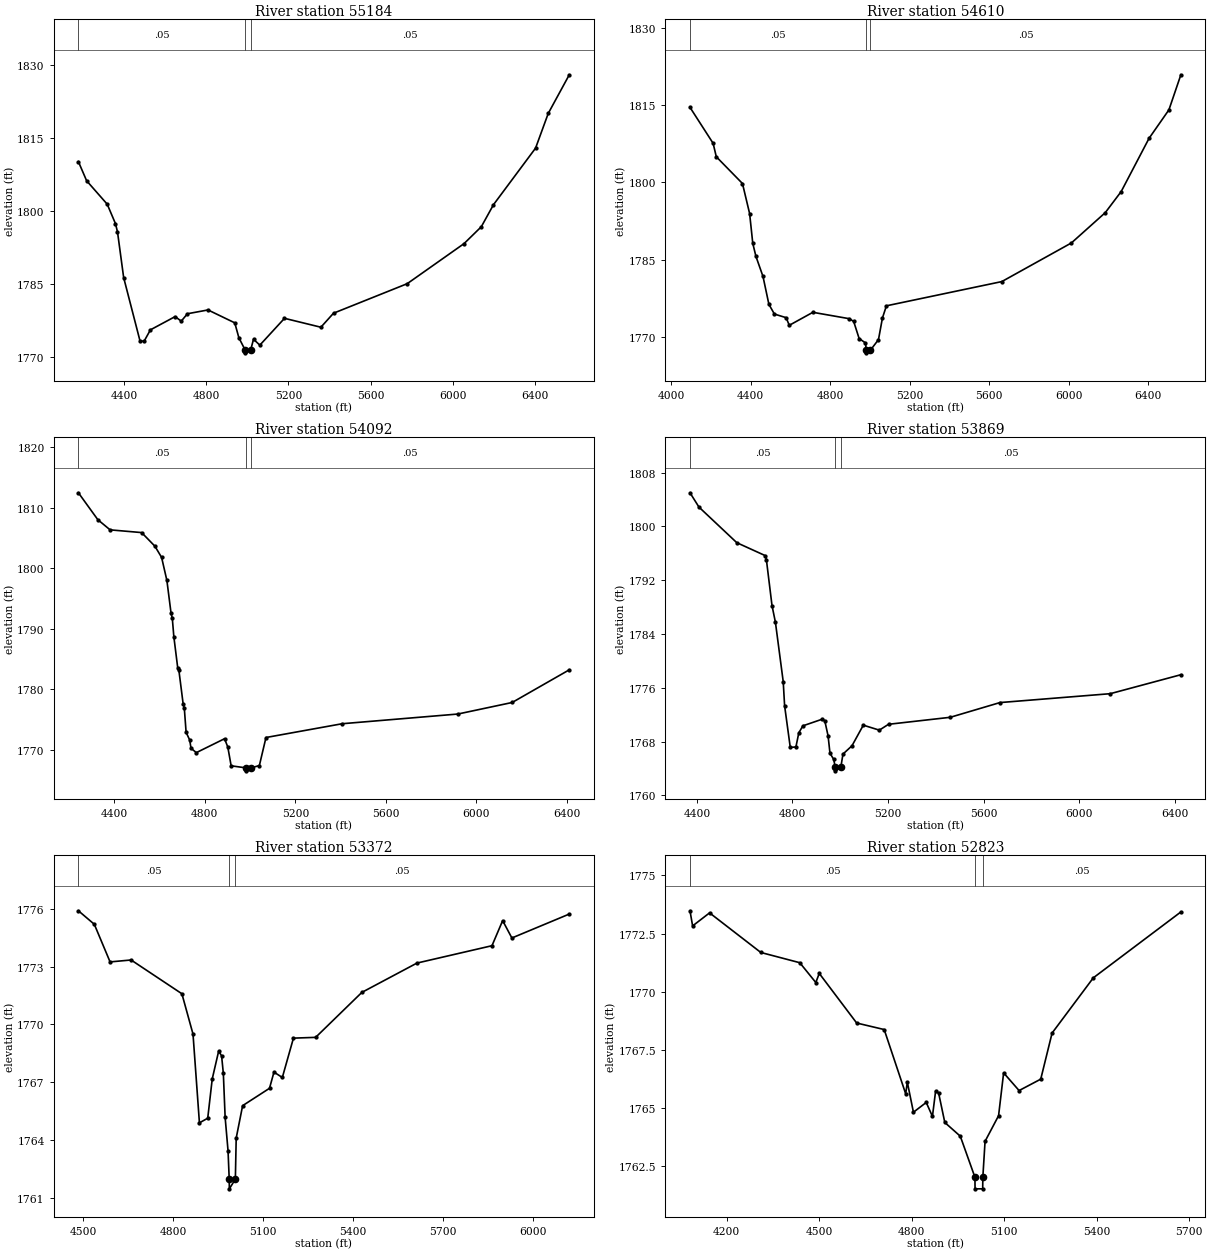
Type RM Length L Ch R = 1,55184,574,574,574
BEGIN DESCRIPTION:
Long Creek 90.0
END DESCRIPTION:
XS GIS Cut Line= 3
      1657705.01      6920688.00      1658505.00      6920738.00
      1660055.03      6921088.01
#Sta/Elev= 30
  4176.9 1810.09  4217.0 1806.16  4317.2 1801.35  4357.2 1797.38  4367.3 1795.67
  4397.3 1786.28  4477.5 1773.18  4497.5 1773.25  4527.6 1775.54  4647.8 1778.26
  4677.9 1777.33  4707.9 1778.85  4808.1 1779.63  4938.4 1776.98  4958.4 1773.92
  4989.9 1771.32  4990.4 1770.82  5015.3 1771.32  5029.7 1773.61  5060.5 1772.40
  5180.6 1777.91  5357.8 1776.08  5419.3 1778.96  5778.1 1785.02  6054.9 1793.25
  6139.1 1796.72  6198.4 1801.25  6403.4 1812.87  6465.0 1819.99  6567.5 1827.93
#Mann=3,-1,0
  4176.9    0.05       0  4989.9    0.03       0  5015.3    0.05       0
Bank Sta=4989.9,5015.3
Exp/Cntr=0.3,0.1

Type RM Length L Ch R = 1,54610,518,518,518
BEGIN DESCRIPTION:
Long Creek 89.0
END DESCRIPTION:
XS GIS Cut Line= 3
      1657605.01      6920838.00      1658405.00      6921288.00
      1659955.02      6921338.00
#Sta/Elev= 30
  4095.5 1814.56  4211.8 1807.59  4227.8 1804.98  4359.4 1799.79  4395.4 1793.96
  4411.3 1788.17  4427.3 1785.64  4462.6 1781.77  4492.3 1776.36  4520.0 1774.47
  4579.0 1773.77  4594.9 1772.29  4713.5 1774.81  4897.0 1773.57  4918.7 1773.04
  4946.1 1769.73  4978.0 1768.87  4982.2 1767.45  4982.6 1766.95  5002.6 1767.45
  5043.4 1769.51  5063.4 1773.72  5083.4 1776.07  5663.7 1780.77  6013.9 1788.27
  6184.0 1794.14  6264.0 1798.23  6404.1 1808.55  6504.1 1814.08  6564.2 1820.88
#Mann=3,-1,0
  4095.5    0.05       0  4982.2    0.03       0  5002.6    0.05       0
Bank Sta=4982.2,5002.6
Exp/Cntr=0.3,0.1

Type RM Length L Ch R = 1,54092,223,223,223
BEGIN DESCRIPTION:
Mapping XS 9d1c1fff
END DESCRIPTION:
XS GIS Cut Line= 3
      1657365.66      6921384.07      1658891.71      6922019.50
      1659407.32      6922035.12
#Sta/Elev= 30
  4241.5 1812.49  4327.4 1808.04  4381.6 1806.36  4520.9 1805.91  4579.5 1803.66
  4609.1 1801.81  4632.5 1797.99  4651.0 1792.54  4656.4 1791.75  4663.2 1788.70
  4680.2 1783.59  4685.6 1783.11  4704.1 1777.65  4709.5 1776.87  4717.4 1772.89
  4733.3 1771.61  4739.1 1770.25  4762.6 1769.53  4887.2 1771.83  4901.6 1770.46
  4916.4 1767.35  4980.6 1767.02  4981.1 1766.52  5006.1 1767.02  5041.1 1767.40
  5070.3 1772.03  5407.3 1774.31  5917.9 1775.91  6158.0 1777.82  6410.4 1783.22
#Mann=3,-1,0
  4241.5    0.05       0  4980.6    0.05       0  5006.1    0.05       0
Bank Sta=4980.6,5006.1
Exp/Cntr=0.3,0.1

Type RM Length L Ch R = 1,53869,497,497,497
BEGIN DESCRIPTION:
Mapping XS c8fcb931
END DESCRIPTION:
XS GIS Cut Line= 4
      1657376.06      6921608.02      1658417.76      6922050.75
      1658896.92      6922201.79      1659301.63      6922310.75
#Sta/Elev= 30
  4371.3 1805.00  4408.9 1802.87  4567.1 1797.58  4685.3 1795.67  4690.8 1795.08
  4714.4 1788.23  4728.7 1785.74  4761.3 1776.92  4767.1 1773.33  4790.8 1767.14
  4814.4 1767.21  4826.5 1769.31  4843.5 1770.35  4925.3 1771.35  4935.2 1771.10
  4949.0 1768.85  4956.9 1766.27  4972.6 1765.36  4979.0 1764.16  4979.5 1763.66
  5002.1 1764.16  5011.2 1766.15  5049.0 1767.39  5096.3 1770.45  5163.3 1769.71
  5201.8 1770.58  5460.0 1771.62  5668.0 1773.81  6129.3 1775.13  6424.7 1777.95
#Mann=3,-1,0
  4371.3    0.05       0  4979.0    0.03       0  5002.1    0.05       0
Bank Sta=4979,5002.1
Exp/Cntr=0.3,0.1

Type RM Length L Ch R = 1,53372,549,549,549
BEGIN DESCRIPTION:
Mapping XS dfdaaa94
END DESCRIPTION:
XS GIS Cut Line= 3
      1657614.01      6922589.89      1658330.16      6922164.54
      1659124.42      6922294.74
#Sta/Elev= 30
  4484.6 1775.89  4537.7 1775.19  4590.3 1773.24  4660.4 1773.34  4829.9 1771.59
  4867.0 1769.50  4888.4 1764.90  4916.1 1765.14  4931.2 1767.18  4952.6 1768.62
  4962.4 1768.37  4968.2 1767.46  4974.2 1765.18  4983.9 1763.45  4987.8 1761.98
  4988.2 1761.48  5008.3 1761.98  5011.1 1764.11  5032.5 1765.79  5122.2 1766.69
  5137.1 1767.53  5165.0 1767.25  5202.1 1769.29  5276.1 1769.33  5430.3 1771.66
  5614.2 1773.18  5864.5 1774.08  5900.1 1775.38  5930.9 1774.48  6122.4 1775.72
#Mann=3,-1,0
  4484.6    0.05       0  4987.8    0.05       0  5008.3    0.05       0
Bank Sta=4987.8,5008.3
Exp/Cntr=0.3,0.1

Type RM Length L Ch R = 1,52823,95,95,95
BEGIN DESCRIPTION:
Mapping XS 40b66b85
END DESCRIPTION:
XS GIS Cut Line= 4
      1657536.91      6922901.95      1658253.58      6922666.14
      1658498.65      6922645.34      1659088.16      6922603.72
#Sta/Elev= 30
  4081.2 1773.48  4089.7 1772.83  4144.7 1773.39  4310.8 1771.69  4437.1 1771.25
  4489.1 1770.40  4500.3 1770.79  4621.6 1768.66  4710.8 1768.38  4780.5 1765.62
  4785.8 1766.12  4805.6 1764.83  4847.1 1765.25  4867.2 1764.65  4877.5 1765.74
  4887.3 1765.65  4907.3 1764.39  4957.5 1763.80  5004.9 1762.04  5005.4 1761.54
  5030.1 1761.54  5030.6 1762.04  5037.8 1763.58  5081.6 1764.68  5098.0 1766.52
  5148.1 1765.76  5218.3 1766.25  5255.1 1768.23  5388.7 1770.60  5672.6 1773.43
#Mann=3,-1,0
  4081.2    0.05       0  5004.9    0.05       0  5030.6    0.05       0
Bank Sta=5004.9,5030.6
Exp/Cntr=0.3,0.1

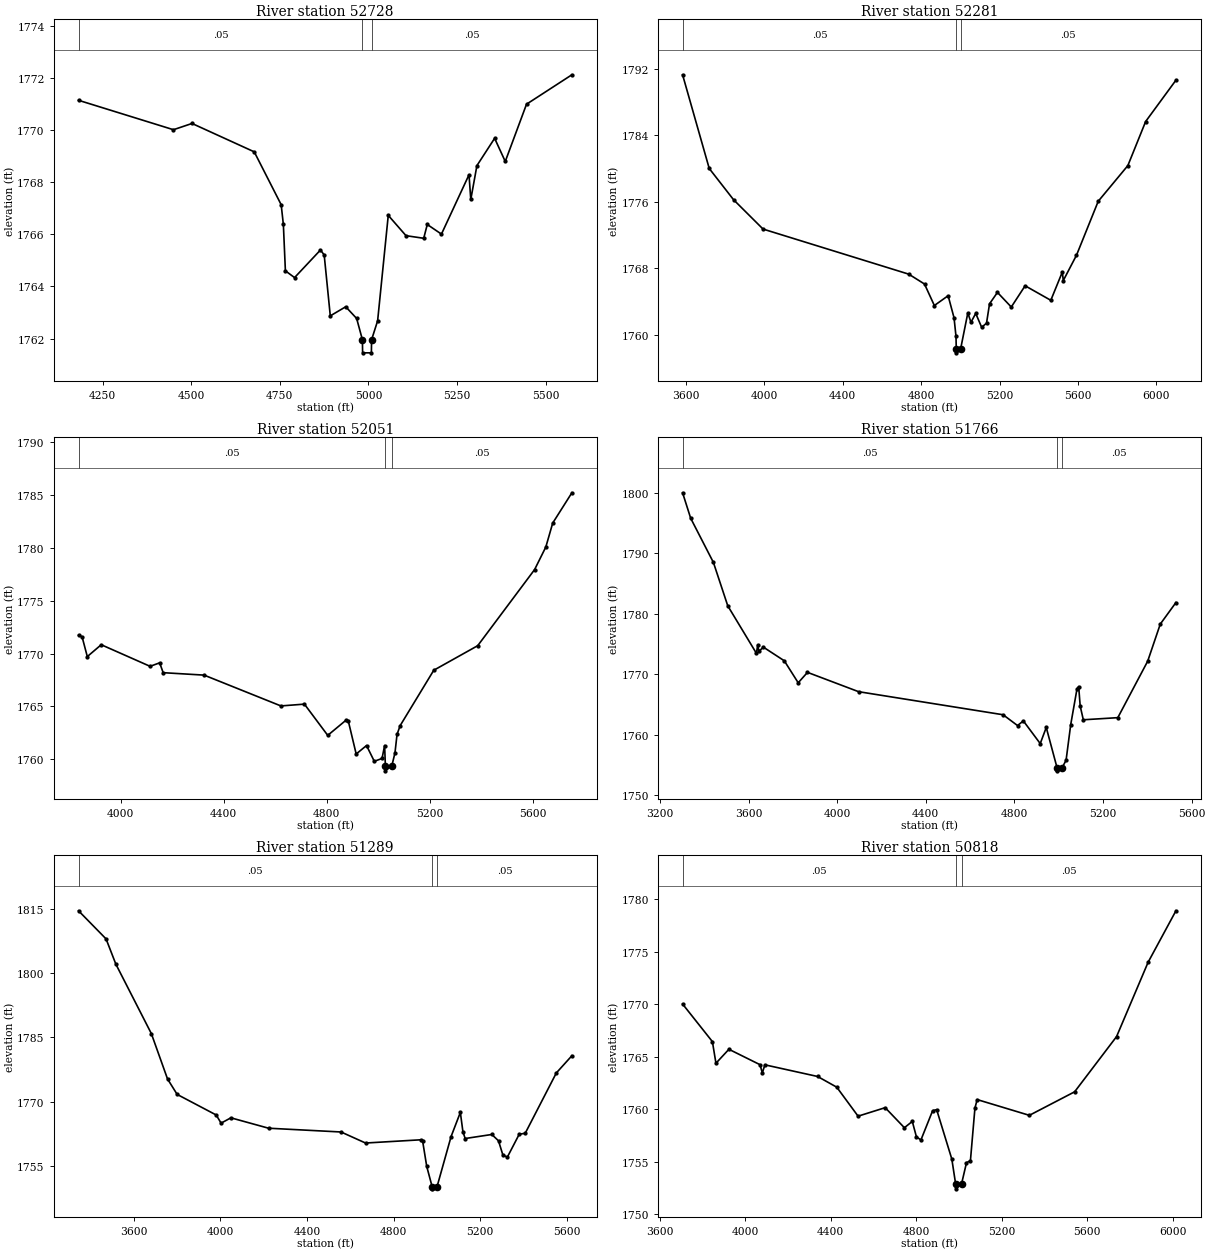
Type RM Length L Ch R = 1,52728,447,447,447
BEGIN DESCRIPTION:
Mapping XS 9df6a5ec
END DESCRIPTION:
XS GIS Cut Line= 5
      1657694.10      6922999.06      1658230.46      6922767.87
      1658353.00      6922730.88      1658951.80      6922749.37
      1659031.38      6922733.46
#Sta/Elev= 30
  4182.0 1771.15  4449.9 1770.02  4502.3 1770.26  4677.9 1769.17  4753.9 1767.14
  4760.1 1766.38  4765.8 1764.60  4791.7 1764.34  4864.8 1765.40  4875.3 1765.21
  4892.5 1762.87  4936.1 1763.22  4966.9 1762.77  4983.2 1761.95  4983.7 1761.45
  5008.5 1761.45  5009.0 1761.95  5026.1 1762.68  5056.1 1766.73  5106.2 1765.95
  5156.2 1765.85  5166.2 1766.38  5206.2 1766.01  5284.0 1768.29  5289.0 1767.34
  5306.3 1768.64  5356.3 1769.69  5386.3 1768.80  5446.3 1771.00  5574.3 1772.13
#Mann=3,-1,0
  4182.0    0.05       0  4983.2    0.05       0  5009.0    0.05       0
Bank Sta=4983.2,5009
Exp/Cntr=0.3,0.1

Type RM Length L Ch R = 1,52281,230,230,230
BEGIN DESCRIPTION:
Long Creek 86.0
END DESCRIPTION:
XS GIS Cut Line= 3
      1657056.28      6922999.60      1658516.71      6923142.33
      1659558.37      6923276.87
#Sta/Elev= 30
  3582.4 1791.31  3718.4 1780.02  3842.4 1776.26  3993.1 1772.72  4736.6 1767.29
  4817.0 1766.10  4867.2 1763.51  4937.5 1764.69  4967.7 1762.03  4977.7 1759.79
  4979.0 1758.31  4979.4 1757.81  5001.5 1758.31  5038.0 1762.62  5054.1 1761.49
  5078.3 1762.56  5108.6 1760.89  5133.4 1761.38  5148.9 1763.72  5189.2 1765.09
  5259.8 1763.33  5330.4 1765.89  5461.5 1764.14  5520.2 1767.54  5525.2 1766.52
  5592.6 1769.57  5703.5 1776.07  5854.7 1780.37  5945.5 1785.68  6100.1 1790.66
#Mann=3,-1,0
  3582.4    0.05       0  4979.0    0.05       0  5001.5    0.05       0
Bank Sta=4979,5001.5
Exp/Cntr=0.3,0.1

Type RM Length L Ch R = 1,52051,285,285,285
BEGIN DESCRIPTION:
Mapping XS cece27af
END DESCRIPTION:
XS GIS Cut Line= 3
      1657411.42      6923167.97      1658285.19      6923322.29
      1659309.08      6923411.96
#Sta/Elev= 30
  3836.6 1771.74  3850.4 1771.58  3870.7 1769.71  3924.8 1770.83  4114.4 1768.79
  4151.5 1769.12  4165.2 1768.19  4324.0 1767.96  4622.2 1765.05  4713.5 1765.22
  4804.0 1762.27  4874.3 1763.69  4884.3 1763.58  4914.4 1760.51  4954.6 1761.31
  4984.7 1759.82  5014.8 1760.09  5024.8 1761.31  5027.7 1759.42  5028.2 1758.92
  5053.1 1759.42  5065.0 1760.62  5073.0 1762.36  5085.1 1763.19  5215.6 1768.42
  5386.2 1770.74  5607.1 1777.93  5650.6 1780.06  5677.3 1782.32  5751.7 1785.18
#Mann=3,-1,0
  3836.6    0.05       0  5027.7    0.05       0  5053.1    0.05       0
Bank Sta=5027.7,5053.1
Exp/Cntr=0.3,0.1

Type RM Length L Ch R = 1,51766,477,477,477
BEGIN DESCRIPTION:
Long Creek 85.0
END DESCRIPTION:
XS GIS Cut Line= 3
      1656936.89      6923081.57      1658555.00      6923588.00
      1658954.99      6923937.99
#Sta/Elev= 30
  3302.1 1799.97  3338.6 1795.77  3441.2 1788.47  3506.1 1781.30  3635.4 1773.46
  3641.2 1774.87  3646.4 1773.79  3666.9 1774.48  3761.2 1772.23  3824.0 1768.60
  3865.9 1770.32  4096.5 1767.13  4748.9 1763.32  4813.9 1761.54  4840.4 1762.30
  4916.5 1758.56  4943.7 1761.22  4992.5 1754.56  4992.9 1754.06  5015.0 1754.56
  5033.2 1755.81  5054.1 1761.69  5082.6 1767.62  5090.1 1767.97  5096.8 1764.77
  5111.0 1762.49  5266.7 1762.84  5401.5 1772.16  5458.4 1778.29  5529.1 1781.85
#Mann=3,-1,0
  3302.1    0.05       0  4992.5    0.03       0  5015.0    0.05       0
Bank Sta=4992.5,5015
Exp/Cntr=0.3,0.1

Type RM Length L Ch R = 1,51289,471,471,471
BEGIN DESCRIPTION:
Long Creek 84.0
END DESCRIPTION:
XS GIS Cut Line= 3
      1656755.00      6923238.00      1658205.00      6923938.00
      1658855.00      6924088.00
#Sta/Elev= 30
  3346.1 1814.49  3473.2 1807.94  3518.4 1802.06  3682.2 1785.89  3757.0 1775.31
  3801.4 1771.72  3981.6 1766.93  4004.2 1765.03  4049.4 1766.27  4223.3 1763.85
  4557.9 1762.97  4670.9 1760.40  4925.1 1761.15  4934.0 1760.98  4953.4 1754.94
  4978.3 1750.23  4978.7 1749.73  5000.9 1750.23  5065.7 1761.90  5108.5 1767.53
  5120.4 1763.03  5130.7 1761.45  5253.8 1762.39  5284.6 1760.92  5305.2 1757.54
  5325.7 1757.14  5380.4 1762.46  5407.8 1762.66  5551.5 1776.72  5623.3 1780.73
#Mann=3,-1,0
  3346.1    0.05       0  4978.3    0.03       0  5000.9    0.05       0
Bank Sta=4978.3,5000.9
Exp/Cntr=0.3,0.1

Type RM Length L Ch R = 1,50818,309,309,309
BEGIN DESCRIPTION:
Long Creek 83.0
END DESCRIPTION:
XS GIS Cut Line= 4
      1657191.74      6923491.81      1657842.75      6923822.52
      1658097.96      6924593.36      1658754.98      6924987.99
#Sta/Elev= 30
  3707.0 1770.00  3846.5 1766.42  3863.1 1764.36  3923.8 1765.69  4069.6 1764.22
  4080.1 1763.43  4092.0 1764.21  4338.8 1763.10  4428.5 1762.08  4528.2 1759.32
  4655.0 1760.13  4744.9 1758.22  4781.9 1758.82  4801.1 1757.36  4822.2 1757.05
  4877.0 1759.84  4895.9 1759.94  4966.9 1755.23  4984.4 1752.90  4984.9 1752.40
  5012.7 1752.90  5035.5 1754.89  5053.9 1755.08  5075.0 1760.09  5085.5 1760.90
  5329.7 1759.40  5541.5 1761.64  5737.8 1766.90  5885.4 1773.98  6015.6 1778.88
#Mann=3,-1,0
  3707.0    0.05       0  4984.4    0.03       0  5012.7    0.05       0
Bank Sta=4984.4,5012.7
Exp/Cntr=0.3,0.1

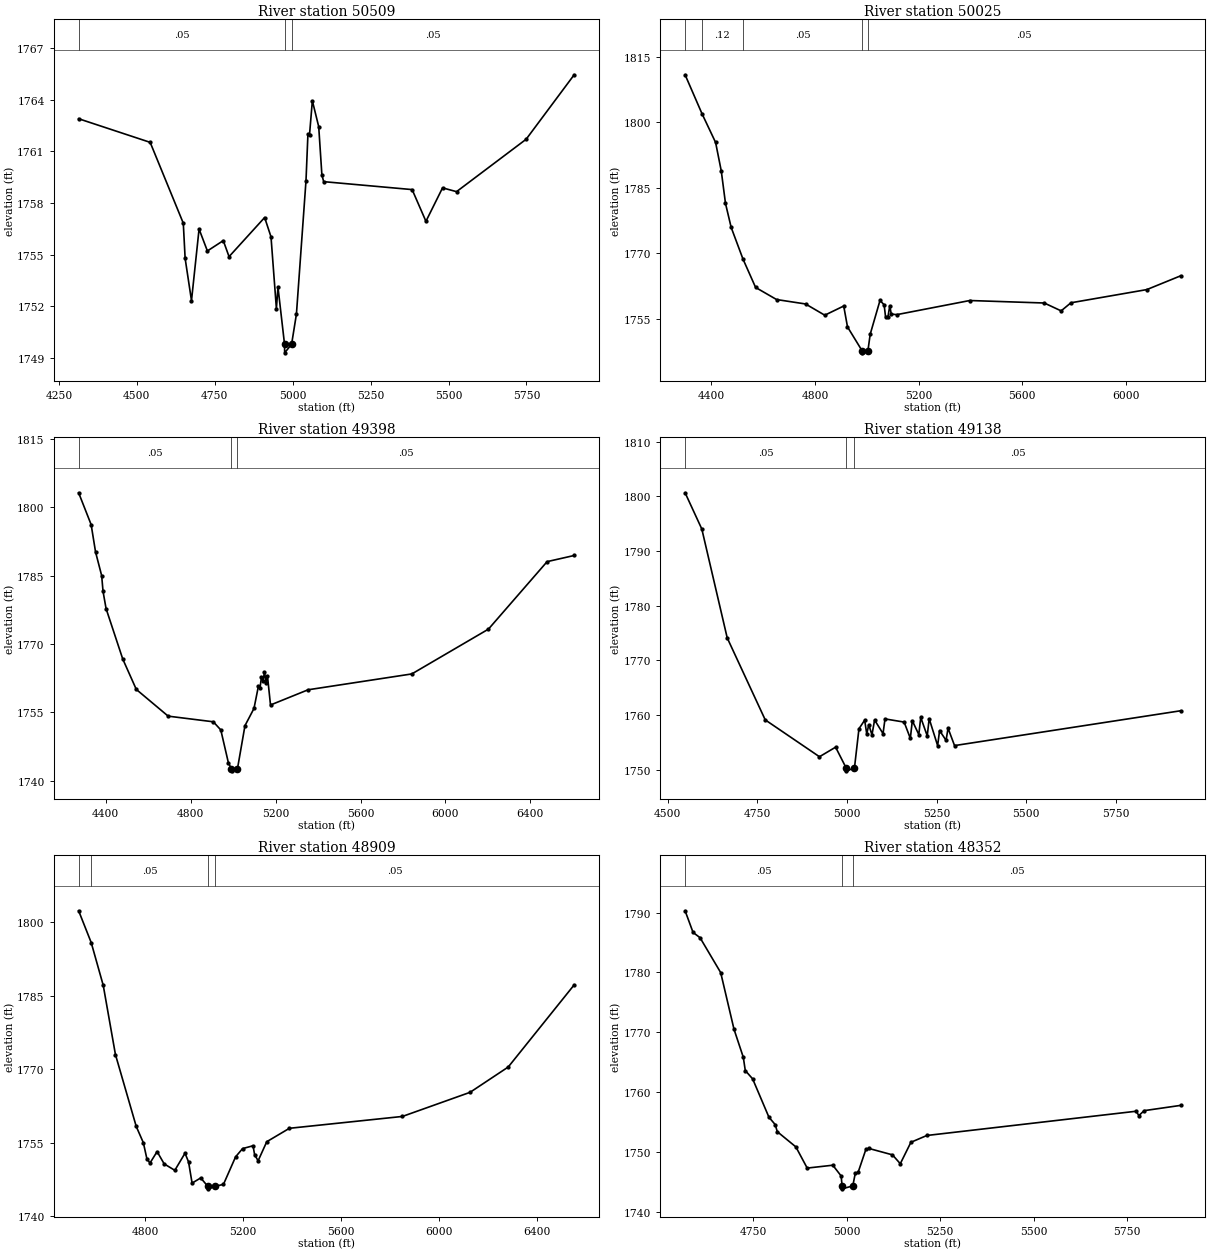
Type RM Length L Ch R = 1,50509,484,484,484
BEGIN DESCRIPTION:
Mapping XS 14d1f56f
END DESCRIPTION:
XS GIS Cut Line= 4
      1657603.29      6923783.14      1657763.86      6924573.47
      1657986.99      6924688.17      1658460.63      6924931.62
#Sta/Elev= 30
  4313.2 1762.89  4542.7 1761.52  4649.0 1756.83  4654.9 1754.79  4675.3 1752.34
  4699.6 1756.49  4726.3 1755.22  4777.3 1755.82  4795.8 1754.89  4910.0 1757.16
  4930.4 1756.04  4947.7 1751.88  4952.8 1753.12  4973.8 1749.81  4974.2 1749.31
  4996.5 1749.81  5012.0 1751.56  5042.7 1759.30  5048.9 1762.00  5054.0 1761.97
  5063.1 1763.93  5083.5 1762.43  5093.7 1759.62  5099.5 1759.24  5383.2 1758.78
  5427.5 1756.94  5480.8 1758.88  5525.7 1758.66  5749.0 1761.70  5903.1 1765.44
#Mann=3,-1,0
  4313.2    0.05       0  4973.8    0.05       0  4996.5    0.05       0
Bank Sta=4973.8,4996.5
Exp/Cntr=0.3,0.1

Type RM Length L Ch R = 1,50025,627,627,627
BEGIN DESCRIPTION:
Long Creek 82.0
END DESCRIPTION:
XS GIS Cut Line= 4
      1656754.99      6924037.99      1657373.33      6924369.28
      1657980.05      6924705.08      1658434.01      6924956.33
#Sta/Elev= 30
  4298.5 1810.83  4363.6 1801.95  4416.3 1795.35  4438.2 1788.83  4454.5 1781.40
  4476.4 1775.92  4521.8 1768.71  4570.8 1762.18  4651.9 1759.41  4763.7 1758.40
  4837.9 1755.83  4911.1 1757.93  4925.7 1753.15  4981.8 1747.72  4982.2 1747.22
  5004.6 1747.72  5013.4 1751.48  5051.2 1759.20  5067.2 1758.21  5072.9 1755.33
  5081.9 1755.44  5089.0 1758.00  5094.7 1756.08  5116.4 1755.96  5398.1 1759.19
  5685.6 1758.62  5750.8 1756.82  5788.6 1758.67  6081.8 1761.69  6212.3 1764.84
#Mann=5,-1,0
  4298.5    0.05       0  4363.6    0.12       0  4521.8    0.05       0
  4981.8    0.03       0  5004.6    0.05       0
Bank Sta=4981.8,5004.6
Exp/Cntr=0.3,0.1

Type RM Length L Ch R = 1,49398,260,260,260
BEGIN DESCRIPTION:
Long Creek 81.0
END DESCRIPTION:
XS GIS Cut Line= 3
      1656709.97      6924340.79      1657142.23      6924872.00
      1658255.02      6926088.02
#Sta/Elev= 30
  4272.8 1803.20  4331.7 1796.21  4352.5 1790.19  4381.3 1785.00  4387.7 1781.55
  4402.1 1777.75  4480.4 1766.71  4544.3 1760.02  4694.4 1754.15  4907.0 1752.91
  4942.2 1751.12  4978.3 1743.83  4992.2 1742.64  4992.7 1742.14  5020.8 1742.64
  5056.0 1752.06  5098.5 1755.85  5119.5 1760.78  5126.9 1760.39  5133.7 1762.73
  5141.1 1761.80  5147.9 1763.89  5155.3 1761.53  5162.0 1762.94  5176.2 1756.60
  5353.2 1759.94  5841.6 1763.42  6202.4 1773.26  6478.6 1788.08  6606.0 1789.43
#Mann=3,-1,0
  4272.8    0.05       0  4992.2    0.05       0  5020.8    0.05       0
Bank Sta=4992.2,5020.8
Exp/Cntr=0.3,0.1

Type RM Length L Ch R = 1,49138,229,229,229
BEGIN DESCRIPTION:
Mapping XS 656c127c
END DESCRIPTION:
XS GIS Cut Line= 5
      1656664.90      6924492.14      1656900.55      6924713.19
      1656998.55      6924888.36      1657100.73      6925126.08
      1657540.37      6925532.37
#Sta/Elev= 30
  4548.9 1800.66  4595.5 1794.03  4666.3 1774.11  4772.3 1759.11  4923.4 1752.37
  4968.4 1754.12  4998.0 1750.29  4998.4 1749.79  5020.9 1750.29  5033.5 1757.49
  5049.4 1759.06  5055.2 1756.55  5060.9 1758.23  5069.7 1756.37  5077.1 1759.09
  5100.6 1756.60  5106.1 1759.29  5159.4 1758.71  5176.7 1755.73  5182.2 1758.95
  5200.3 1756.43  5205.7 1759.56  5223.8 1756.19  5229.2 1759.33  5252.8 1754.40
  5258.2 1757.16  5276.3 1755.36  5281.8 1757.59  5299.9 1754.41  5930.1 1760.78
#Mann=3,-1,0
  4548.9    0.05       0  4998.0    0.03       0  5020.9    0.05       0
Bank Sta=4998,5020.9
Exp/Cntr=0.3,0.1

Type RM Length L Ch R = 1,48909,557,557,557
BEGIN DESCRIPTION:
Long Creek 80.0
END DESCRIPTION:
XS GIS Cut Line= 3
      1656504.97      6924737.98      1656955.00      6925088.00
      1658055.02      6926038.02
#Sta/Elev= 30
  4529.4 1802.36  4580.7 1795.87  4629.9 1787.12  4679.7 1772.99  4764.7 1758.29
  4793.7 1754.97  4808.1 1751.70  4820.8 1750.82  4849.8 1753.16  4878.7 1750.65
  4922.2 1749.33  4963.8 1752.83  4978.3 1751.05  4992.7 1746.72  5028.0 1747.78
  5057.1 1746.05  5057.6 1745.55  5085.8 1746.05  5120.9 1746.47  5170.3 1752.08
  5198.8 1753.77  5241.6 1754.35  5248.2 1752.49  5262.4 1751.29  5297.7 1755.18
  5390.2 1757.92  5851.5 1760.34  6127.9 1765.27  6283.7 1770.44  6553.0 1787.22
#Mann=4,-1,0
  4529.4    0.12       0  4580.7    0.05       0  5057.1    0.03       0
  5085.8    0.05       0
Bank Sta=5057.1,5085.8
Exp/Cntr=0.3,0.1

Type RM Length L Ch R = 1,48352,271,271,271
BEGIN DESCRIPTION:
Long Creek 79.0
END DESCRIPTION:
XS GIS Cut Line= 3
      1656405.02      6924988.04      1656555.00      6925388.00
      1657227.62      6925983.49
#Sta/Elev= 30
  4567.6 1790.29  4588.9 1786.67  4607.6 1785.79  4662.8 1779.96  4698.4 1770.49
  4723.3 1765.80  4728.6 1763.58  4748.2 1762.20  4791.8 1755.79  4808.7 1754.54
  4814.1 1753.37  4863.9 1750.82  4894.2 1747.28  4962.7 1747.76  4985.0 1745.96
  4987.5 1744.31  4988.0 1743.81  5016.2 1744.31  5022.8 1746.40  5030.3 1746.55
  5051.2 1750.41  5058.7 1750.57  5122.3 1749.49  5143.2 1748.01  5171.6 1751.59
  5214.3 1752.73  5773.9 1756.78  5781.4 1756.06  5795.6 1756.88  5893.1 1757.76
#Mann=3,-1,0
  4567.6    0.05       0  4987.5    0.03       0  5016.2    0.05       0
Bank Sta=4987.5,5016.2
Exp/Cntr=0.3,0.1

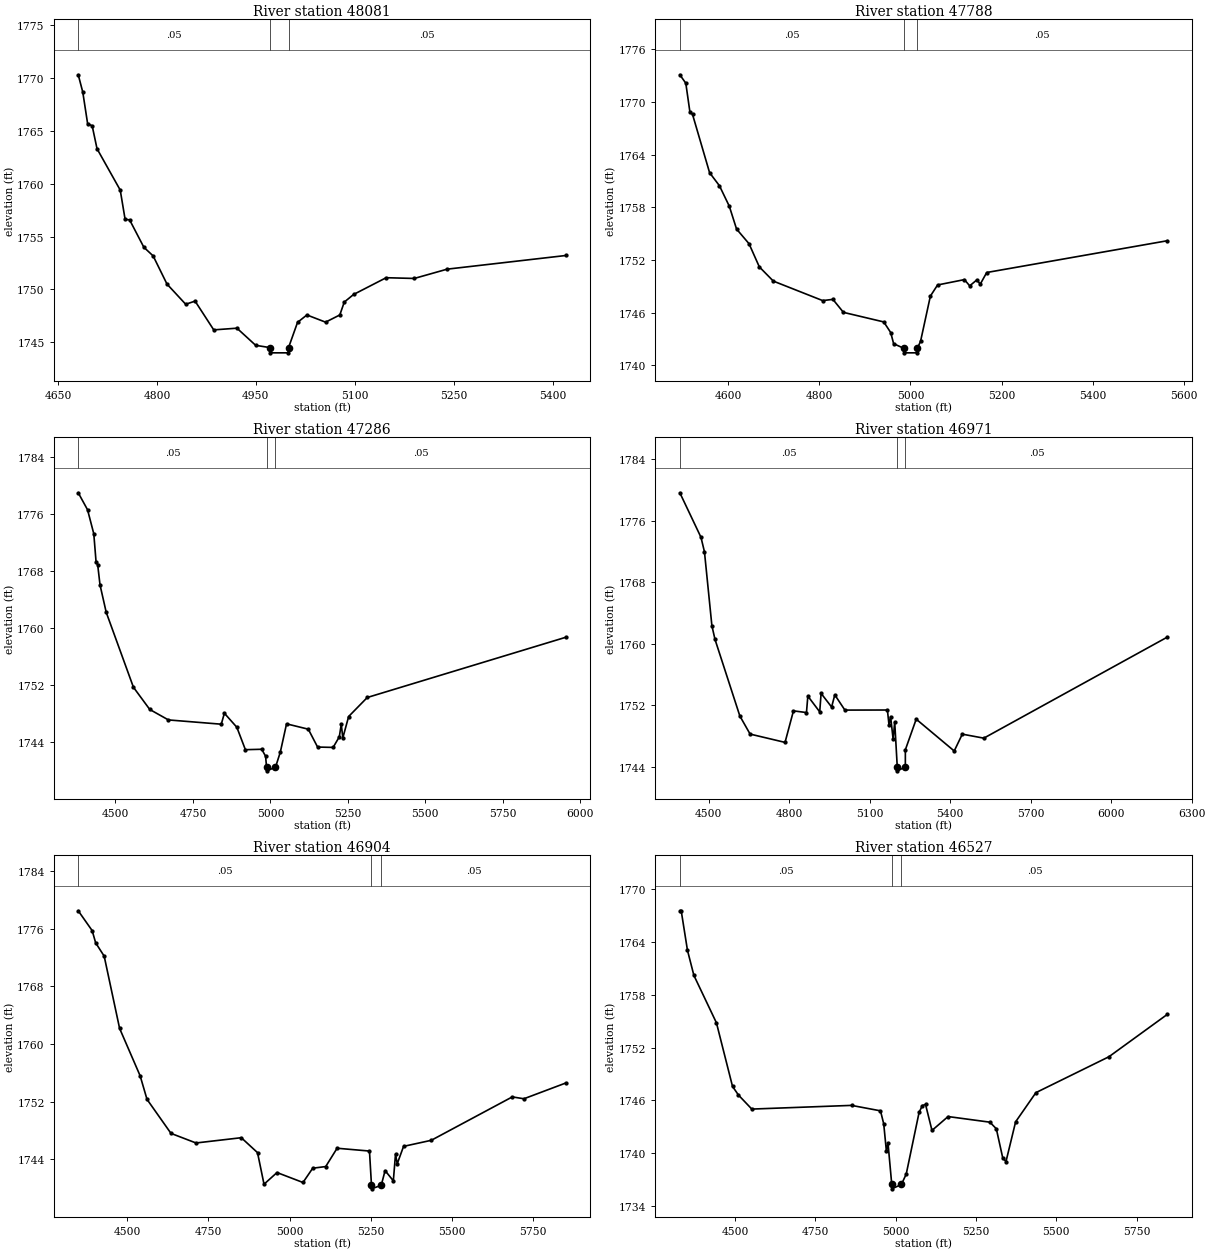
Type RM Length L Ch R = 1,48081,293,293,293
BEGIN DESCRIPTION:
Mapping XS e8409ba4
END DESCRIPTION:
XS GIS Cut Line= 2
      1656149.84      6925342.95      1656648.21      6925889.29
#Sta/Elev= 30
  4680.7 1770.29  4687.6 1768.65  4695.0 1765.64  4701.8 1765.48  4709.2 1763.30
  4744.4 1759.39  4751.8 1756.62  4758.6 1756.58  4780.2 1753.99  4794.3 1753.17
  4815.3 1750.51  4843.7 1748.60  4857.9 1748.90  4886.2 1746.18  4921.4 1746.34
  4949.8 1744.72  4971.0 1744.51  4971.5 1744.01  4999.2 1744.01  4999.7 1744.51
  5013.3 1746.89  5027.5 1747.59  5055.8 1746.91  5077.4 1747.59  5084.2 1748.81
  5098.4 1749.53  5147.7 1751.11  5190.3 1751.04  5240.3 1751.92  5420.2 1753.21
#Mann=3,-1,0
  4680.7    0.05       0  4971.0    0.05       0  4999.7    0.05       0
Bank Sta=4971,4999.7
Exp/Cntr=0.3,0.1

Type RM Length L Ch R = 1,47788,502,502,502
BEGIN DESCRIPTION:
Long Creek 78.0
END DESCRIPTION:
XS GIS Cut Line= 3
      1655897.49      6925336.66      1656155.00      6925788.00
      1656630.00      6926063.00
#Sta/Elev= 30
  4494.7 1773.11  4507.8 1772.15  4516.7 1768.90  4522.5 1768.60  4559.9 1761.96
  4581.5 1760.47  4603.1 1758.14  4619.0 1755.54  4646.3 1753.87  4668.9 1751.23
  4699.6 1749.61  4807.7 1747.39  4830.1 1747.53  4853.2 1746.05  4941.6 1744.96
  4956.8 1743.75  4963.2 1742.48  4986.3 1741.94  4986.8 1741.44  5014.5 1741.44
  5015.0 1741.94  5022.2 1742.75  5043.7 1747.90  5059.5 1749.17  5118.3 1749.78
  5129.9 1749.07  5145.6 1749.75  5153.0 1749.26  5167.2 1750.59  5563.2 1754.21
#Mann=3,-1,0
  4494.7    0.05       0  4986.3    0.05       0  5015.0    0.05       0
Bank Sta=4986.3,5015
Exp/Cntr=0.3,0.1

Type RM Length L Ch R = 1,47286,315,315,315
BEGIN DESCRIPTION:
Long Creek 77.0
END DESCRIPTION:
XS GIS Cut Line= 3
      1655655.00      6925337.98      1655705.00      6925938.00
      1655763.76      6926907.62
#Sta/Elev= 30
  4379.8 1778.97  4409.9 1776.58  4430.0 1773.21  4437.5 1769.18  4442.5 1768.89
  4450.1 1766.03  4470.1 1762.18  4557.9 1751.66  4610.6 1748.54  4670.8 1747.07
  4841.4 1746.47  4851.4 1748.01  4891.6 1746.04  4919.2 1742.89  4971.9 1742.95
  4984.4 1741.97  4987.5 1740.42  4988.0 1739.92  5016.3 1740.42  5032.0 1742.56
  5052.0 1746.52  5122.2 1745.77  5152.2 1743.26  5202.3 1743.21  5222.3 1744.70
  5228.6 1746.47  5233.6 1744.54  5252.4 1747.55  5312.5 1750.22  5953.3 1758.68
#Mann=3,-1,0
  4379.8    0.05       0  4987.5    0.03       0  5016.3    0.05       0
Bank Sta=4987.5,5016.3
Exp/Cntr=0.3,0.1

Type RM Length L Ch R = 1,46971,67,67,67
BEGIN DESCRIPTION:
Mapping XS 6a6598b4
END DESCRIPTION:
XS GIS Cut Line= 6
      1655575.76      6925302.59      1655396.06      6925961.46
      1655406.48      6926031.78      1655437.73      6926081.26
      1655531.48      6926109.90      1655471.58      6927010.93
#Sta/Elev= 30
  4392.3 1779.63  4471.1 1773.84  4484.1 1771.95  4511.8 1762.34  4523.3 1760.57
  4616.0 1750.60  4654.2 1748.25  4784.4 1747.17  4815.8 1751.27  4864.3 1751.05
  4869.4 1753.19  4913.7 1751.14  4918.8 1753.54  4958.0 1751.77  4969.9 1753.35
  5007.5 1751.37  5166.0 1751.38  5172.0 1749.41  5177.9 1750.52  5187.3 1747.58
  5193.2 1749.82  5202.7 1743.97  5203.2 1743.47  5232.8 1743.97  5232.9 1746.21
  5273.3 1750.19  5415.0 1746.05  5445.1 1748.24  5525.3 1747.72  6209.7 1760.87
#Mann=3,-1,0
  4392.3    0.05       0  5202.7    0.03       0  5232.8    0.05       0
Bank Sta=5202.7,5232.8
Exp/Cntr=0.3,0.1

Type RM Length L Ch R = 1,46904,377,377,377
BEGIN DESCRIPTION:
Mapping XS 5c044ec4
END DESCRIPTION:
XS GIS Cut Line= 5
      1655475.60      6925257.34      1655344.64      6925644.23
      1655344.64      6926033.21      1655433.18      6926309.25
      1655344.92      6926714.22
#Sta/Elev= 30
  4348.8 1778.49  4391.7 1775.74  4402.5 1774.04  4428.7 1772.20  4476.2 1762.18
  4539.5 1755.60  4560.6 1752.34  4634.5 1747.62  4711.5 1746.29  4851.0 1747.02
  4901.0 1744.95  4921.0 1740.57  4961.0 1742.19  5041.0 1740.81  5071.0 1742.79
  5111.0 1743.02  5146.1 1745.56  5245.8 1745.17  5252.0 1740.43  5252.5 1739.93
  5282.1 1740.43  5293.9 1742.46  5319.3 1741.04  5326.0 1744.74  5331.3 1743.41
  5350.8 1745.82  5436.1 1746.66  5685.7 1752.68  5721.4 1752.42  5850.6 1754.61
#Mann=3,-1,0
  4348.8    0.05       0  5252.0    0.03       0  5282.1    0.05       0
Bank Sta=5252,5282.1
Exp/Cntr=0.3,0.1

Type RM Length L Ch R = 1,46527,497,497,497
BEGIN DESCRIPTION:
Mapping XS 50a30775
END DESCRIPTION:
XS GIS Cut Line= 2
      1655032.14      6925184.29      1654933.18      6926699.86
#Sta/Elev= 30
  4327.5 1767.56  4331.8 1767.56  4351.3 1763.06  4371.3 1760.21  4441.5 1754.82
  4491.6 1747.59  4510.2 1746.60  4551.7 1745.01  4862.3 1745.43  4952.5 1744.81
  4962.6 1743.33  4970.9 1740.22  4975.9 1741.15  4987.6 1736.44  4988.1 1735.94
  5017.7 1736.44  5032.7 1737.62  5072.8 1744.64  5082.8 1745.40  5092.8 1745.54
  5112.9 1742.58  5163.0 1744.16  5293.3 1743.52  5313.3 1742.77  5333.3 1739.46
  5343.4 1739.04  5373.4 1743.56  5436.6 1746.88  5664.0 1750.96  5846.3 1755.79
#Mann=3,-1,0
  4327.5    0.05       0  4987.6    0.03       0  5017.7    0.05       0
Bank Sta=4987.6,5017.7
Exp/Cntr=0.3,0.1

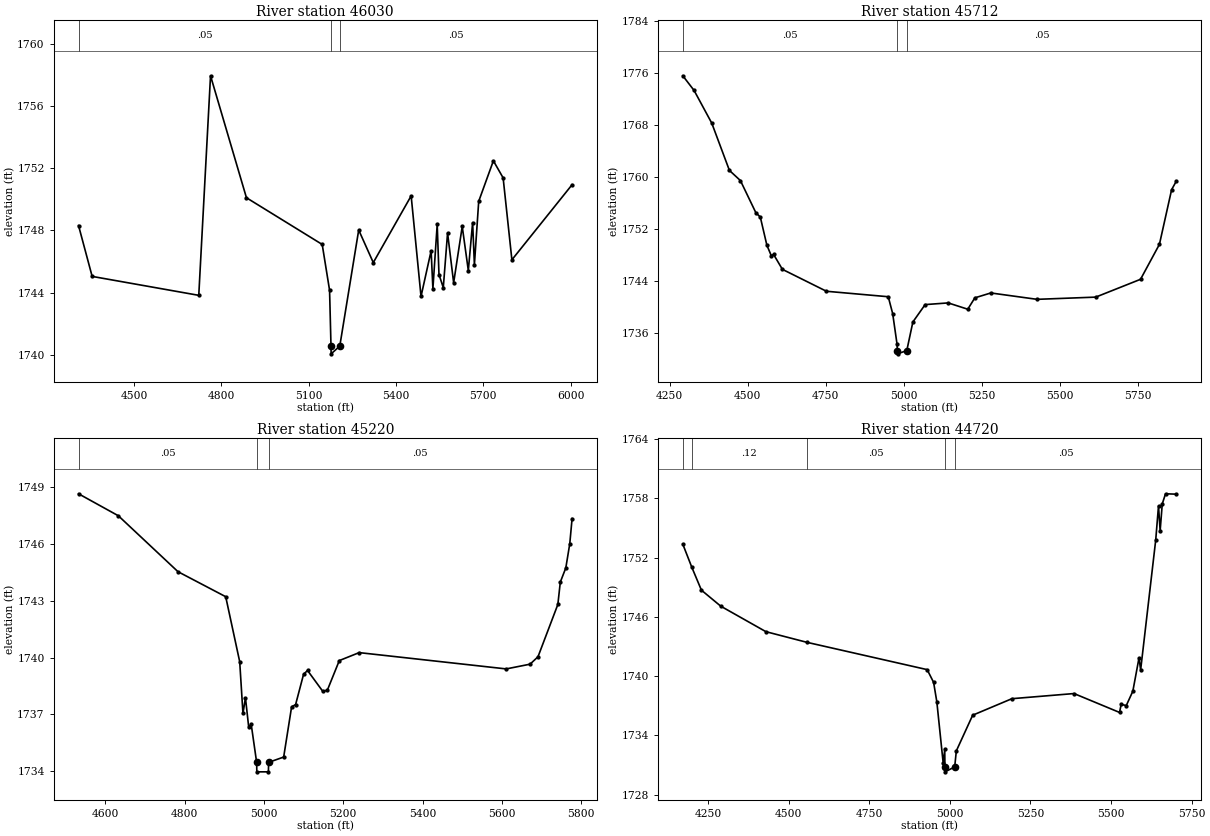
Type RM Length L Ch R = 1,46030,318,318,318
BEGIN DESCRIPTION:
Mapping XS 615f0f30
END DESCRIPTION:
XS GIS Cut Line= 6
      1654946.61      6925307.52      1654892.39      6925695.37
      1654448.22      6925749.59      1654441.97      6926076.98
      1654667.18      6926237.55      1654650.59      6926484.33
#Sta/Elev= 30
  4309.3 1748.32  4356.1 1745.04  4722.4 1743.82  4762.8 1757.97  4886.2 1750.11
  5146.5 1747.10  5171.8 1744.15  5176.7 1740.55  5177.2 1740.05  5206.9 1740.55
  5271.9 1748.03  5322.0 1745.93  5452.1 1750.23  5486.0 1743.75  5520.7 1746.69
  5526.8 1744.25  5541.6 1748.39  5547.7 1745.16  5562.5 1744.32  5577.2 1747.84
  5598.1 1744.63  5627.6 1748.26  5648.5 1745.42  5663.3 1748.51  5669.4 1745.80
  5684.2 1749.88  5734.6 1752.49  5768.1 1751.39  5798.2 1746.11  6005.0 1750.95
#Mann=3,-1,0
  4309.3    0.05       0  5176.7    0.03       0  5206.9    0.05       0
Bank Sta=5176.7,5206.9
Exp/Cntr=0.3,0.1

Type RM Length L Ch R = 1,45712,492,492,492
BEGIN DESCRIPTION:
Long Creek 74.0
END DESCRIPTION:
XS GIS Cut Line= 3
      1654965.18      6924977.01      1654465.15      6925459.67
      1654086.66      6926261.78
#Sta/Elev= 30
  4291.8 1775.55  4328.0 1773.29  4384.6 1768.27  4441.2 1761.00  4476.4 1759.44
  4526.1 1754.48  4540.2 1753.83  4561.3 1749.49  4575.5 1747.88  4582.7 1748.09
  4611.0 1745.79  4752.2 1742.42  4950.3 1741.58  4964.5 1738.98  4978.6 1734.24
  4979.5 1733.30  4980.0 1732.80  5009.7 1733.30  5029.2 1737.70  5068.5 1740.37
  5142.4 1740.63  5205.1 1739.66  5227.9 1741.41  5279.0 1742.16  5427.2 1741.18
  5615.2 1741.52  5758.9 1744.26  5819.4 1749.63  5858.5 1758.04  5873.7 1759.36
#Mann=3,-1,0
  4291.8    0.05       0  4979.5    0.03       0  5009.7    0.05       0
Bank Sta=4979.5,5009.7
Exp/Cntr=0.3,0.1

Type RM Length L Ch R = 1,45220,500,500,500
BEGIN DESCRIPTION:
Long Creek 73.0
END DESCRIPTION:
XS GIS Cut Line= 3
      1654306.60      6924968.63      1654020.22      6925338.52
      1653968.08      6926113.77
#Sta/Elev= 30
  4532.2 1748.64  4632.6 1747.48  4783.0 1744.53  4903.4 1743.21  4938.7 1739.78
  4946.9 1737.05  4953.2 1737.87  4961.4 1736.33  4967.7 1736.48  4981.4 1734.47
  4981.9 1733.97  5011.1 1733.97  5011.6 1734.47  5049.6 1734.75  5069.6 1737.40
  5079.7 1737.52  5099.7 1739.11  5109.7 1739.32  5148.5 1738.21  5159.8 1738.28
  5189.9 1739.84  5240.0 1740.26  5610.9 1739.40  5671.0 1739.65  5691.0 1740.04
  5741.1 1742.80  5747.3 1743.98  5761.2 1744.73  5771.2 1746.01  5777.0 1747.33
#Mann=3,-1,0
  4532.2    0.05       0  4981.4    0.03       0  5011.6    0.05       0
Bank Sta=4981.4,5011.6
Exp/Cntr=0.3,0.1

Type RM Length L Ch R = 1,44720,458,458,458
BEGIN DESCRIPTION:
Long Creek 72.0
END DESCRIPTION:
XS GIS Cut Line= 3
      1653568.38      6924520.35      1653539.81      6925337.47
      1653658.64      6926041.09
#Sta/Elev= 30
  4171.4 1753.35  4199.4 1751.01  4229.1 1748.70  4289.1 1747.08  4429.2 1744.50
  4555.5 1743.43  4929.5 1740.66  4949.5 1739.37  4959.5 1737.40  4979.1 1731.24
  4984.1 1732.59  4984.5 1730.82  4985.0 1730.32  5014.9 1730.82  5020.0 1732.44
  5070.7 1736.05  5192.4 1737.72  5385.1 1738.24  5526.3 1736.33  5531.4 1737.14
  5547.3 1737.03  5567.6 1738.48  5586.8 1741.86  5591.8 1740.63  5638.6 1753.78
  5647.2 1757.22  5652.3 1754.71  5658.9 1757.43  5669.0 1758.45  5702.6 1758.41
#Mann=5,-1,0
  4171.4    0.05       0  4199.4    0.12       0  4555.5    0.05       0
  4984.5    0.05       0  5014.9    0.05       0
Bank Sta=4984.5,5014.9
Exp/Cntr=0.3,0.1