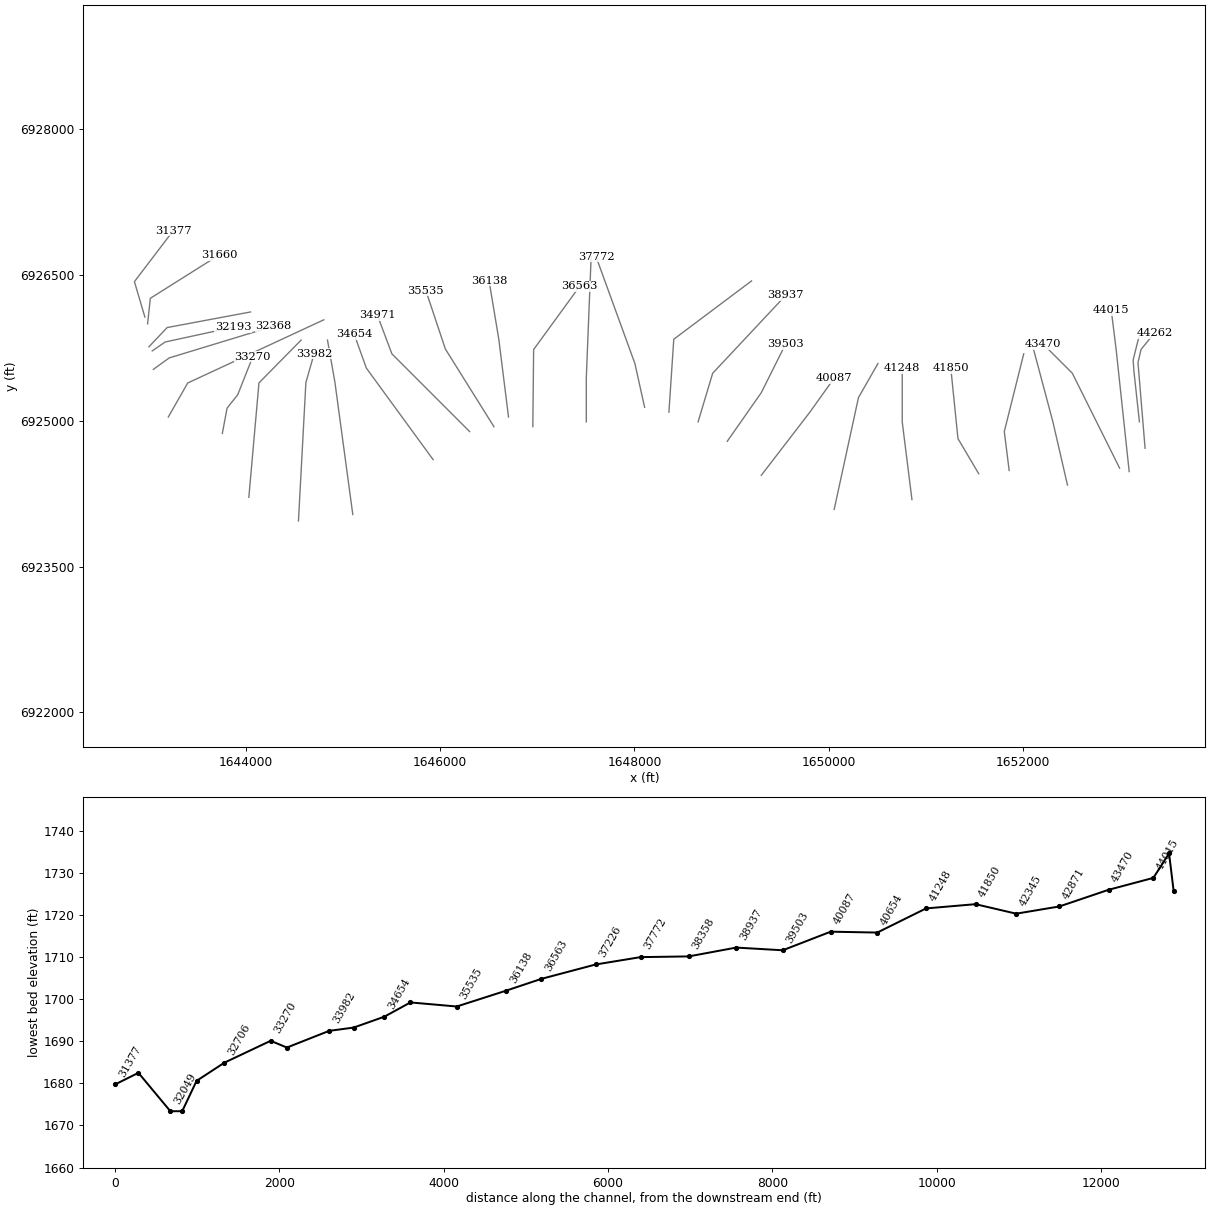
HEC-RAS study Long Creek.prj: Long Creek Base Level Engineering

--- Long Creek.g01 (geometry) --- (continued)

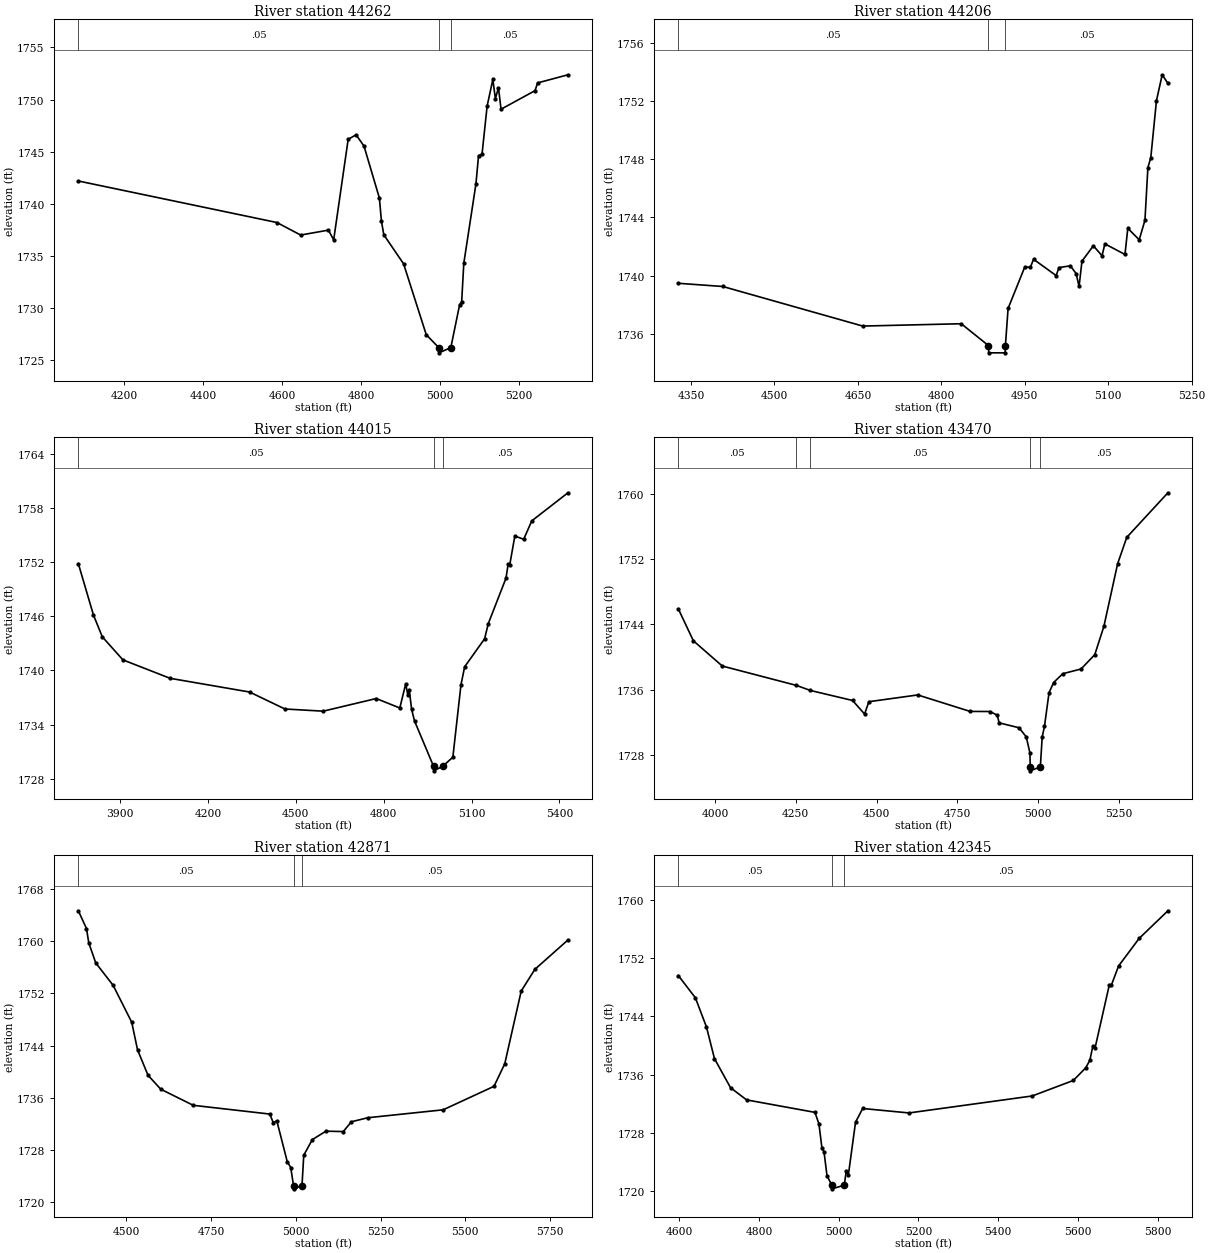
Type RM Length L Ch R = 1,44262,56,56,56
BEGIN DESCRIPTION:
Mapping XS 435a6554
END DESCRIPTION:
XS GIS Cut Line= 5
      1653253.22      6924716.39      1653226.23      6925042.67
      1653180.36      6925597.36      1653211.64      6925732.90
      1653349.29      6925901.84
#Sta/Elev= 30
  4083.3 1742.20  4586.6 1738.22  4646.8 1737.02  4717.1 1737.49  4730.5 1736.56
  4767.2 1746.19  4787.3 1746.63  4807.4 1745.54  4846.4 1740.56  4851.4 1738.40
  4857.5 1737.05  4907.7 1734.26  4965.1 1727.47  4996.9 1726.23  4997.4 1725.73
  5027.4 1726.23  5049.8 1730.36  5054.9 1730.62  5060.3 1734.31  5091.1 1741.93
  5097.7 1744.64  5106.4 1744.74  5119.5 1749.40  5133.9 1751.93  5140.3 1750.10
  5148.2 1751.13  5154.7 1749.08  5240.9 1750.86  5247.3 1751.60  5324.3 1752.38
#Mann=3,-1,0
  4083.3    0.05       0  4996.9    0.05       0  5027.4    0.05       0
Bank Sta=4996.9,5027.4
Exp/Cntr=0.3,0.1

Type RM Length L Ch R = 1,44206,191,191,191
BEGIN DESCRIPTION:
Mapping XS 75ef4cda
END DESCRIPTION:
XS GIS Cut Line= 4
      1653194.95      6924988.46      1653138.65      6925507.69
      1653130.31      6925624.47      1653188.70      6925858.03
#Sta/Elev= 30
  4327.1 1739.47  4407.1 1739.25  4658.6 1736.53  4835.7 1736.69  4884.6 1735.19
  4885.1 1734.69  4914.6 1734.69  4915.1 1735.19  4919.9 1737.74  4949.9 1740.59
  4960.0 1740.57  4965.7 1741.12  5006.3 1740.00  5011.4 1740.55  5031.9 1740.67
  5042.2 1740.14  5047.5 1739.25  5052.7 1740.99  5073.2 1742.05  5088.8 1741.36
  5093.9 1742.18  5130.0 1741.45  5135.1 1743.25  5155.6 1742.46  5165.9 1743.80
  5171.2 1747.42  5176.4 1748.10  5186.6 1752.02  5196.9 1753.80  5207.2 1753.21
#Mann=3,-1,0
  4327.1    0.05       0  4884.6    0.05       0  4915.1    0.05       0
Bank Sta=4884.6,4915.1
Exp/Cntr=0.3,0.1

Type RM Length L Ch R = 1,44015,545,545,545
BEGIN DESCRIPTION:
Long Creek 71.0
END DESCRIPTION:
XS GIS Cut Line= 3
      1653089.75      6924476.59      1652955.00      6925738.00
      1652905.00      6926138.00
#Sta/Elev= 30
  3757.4 1751.82  3809.1 1746.12  3839.3 1743.71  3909.7 1741.16  4070.6 1739.12
  4342.1 1737.60  4462.8 1735.72  4593.5 1735.48  4774.6 1736.88  4855.0 1735.83
  4875.1 1738.50  4882.5 1737.27  4887.5 1737.78  4895.2 1735.69  4905.3 1734.39
  4970.3 1729.37  4970.8 1728.87  5001.3 1729.37  5036.1 1730.38  5063.8 1738.39
  5076.4 1740.40  5144.4 1743.49  5157.0 1745.17  5217.5 1750.21  5225.0 1751.78
  5230.1 1751.64  5247.7 1754.88  5277.9 1754.52  5305.6 1756.56  5429.1 1759.67
#Mann=3,-1,0
  3757.4    0.05       0  4970.3    0.05       0  5001.3    0.05       0
Bank Sta=4970.3,5001.3
Exp/Cntr=0.3,0.1

Type RM Length L Ch R = 1,43470,599,599,599
BEGIN DESCRIPTION:
Long Creek 70.0
END DESCRIPTION:
XS GIS Cut Line= 3
      1652991.29      6924512.16      1652505.00      6925488.00
      1652204.97      6925788.03
#Sta/Elev= 30
  3886.7 1745.89  3933.4 1741.97  4022.9 1738.88  4252.0 1736.51  4295.2 1735.89
  4425.8 1734.66  4463.0 1733.00  4476.2 1734.51  4627.3 1735.34  4789.5 1733.32
  4851.1 1733.31  4873.5 1732.85  4879.1 1731.92  4940.6 1731.32  4963.0 1730.21
  4974.2 1728.27  4975.6 1726.54  4976.1 1726.04  5006.7 1726.54  5012.4 1730.20
  5019.4 1731.49  5033.6 1735.62  5047.7 1736.86  5076.0 1737.94  5132.6 1738.52
  5175.0 1740.27  5203.3 1743.75  5245.7 1751.41  5274.0 1754.65  5401.3 1760.11
#Mann=5,-1,0
  3886.7    0.05       0  4252.0    0.12       0  4295.2    0.05       0
  4975.6    0.05       0  5006.7    0.05       0
Bank Sta=4975.6,5006.7
Exp/Cntr=0.3,0.1

Type RM Length L Ch R = 1,42871,526,526,526
BEGIN DESCRIPTION:
Long Creek 69.0
END DESCRIPTION:
XS GIS Cut Line= 3
      1652455.01      6924337.97      1652305.00      6924988.00
      1652105.01      6925737.98
#Sta/Elev= 30
  4359.2 1764.66  4383.2 1761.94  4390.0 1759.74  4410.5 1756.68  4461.9 1753.23
  4516.6 1747.59  4533.7 1743.37  4564.5 1739.48  4602.1 1737.34  4697.9 1734.87
  4923.7 1733.53  4933.9 1732.19  4944.2 1732.51  4975.0 1726.25  4985.3 1725.34
  4993.5 1722.58  4993.9 1722.08  5018.5 1722.58  5023.7 1727.23  5049.0 1729.62
  5089.1 1730.91  5140.2 1730.85  5164.1 1732.35  5212.6 1732.97  5434.5 1734.18
  5584.5 1737.78  5616.2 1741.23  5664.7 1752.37  5704.9 1755.69  5802.5 1760.19
#Mann=3,-1,0
  4359.2    0.05       0  4993.5    0.05       0  5018.5    0.05       0
Bank Sta=4993.5,5018.5
Exp/Cntr=0.3,0.1

Type RM Length L Ch R = 1,42345,495,495,495
BEGIN DESCRIPTION:
Long Creek 68.0
END DESCRIPTION:
XS GIS Cut Line= 3
      1651855.00      6924487.99      1651805.00      6924888.00
      1652004.99      6925687.95
#Sta/Elev= 30
  4597.7 1749.62  4640.5 1746.57  4668.3 1742.57  4688.4 1738.22  4728.7 1734.23
  4769.0 1732.56  4940.4 1730.85  4950.4 1729.25  4958.0 1725.90  4963.0 1725.47
  4970.6 1722.15  4982.7 1720.86  4983.2 1720.36  5013.9 1720.86  5018.9 1722.84
  5024.0 1722.20  5042.1 1729.50  5060.1 1731.38  5176.1 1730.77  5485.3 1733.10
  5588.4 1735.23  5619.3 1736.96  5629.6 1737.98  5637.3 1739.97  5642.5 1739.63
  5678.6 1748.37  5683.7 1748.31  5701.8 1750.94  5753.3 1754.71  5825.4 1758.50
#Mann=3,-1,0
  4597.7    0.05       0  4982.7    0.05       0  5013.9    0.05       0
Bank Sta=4982.7,5013.9
Exp/Cntr=0.3,0.1

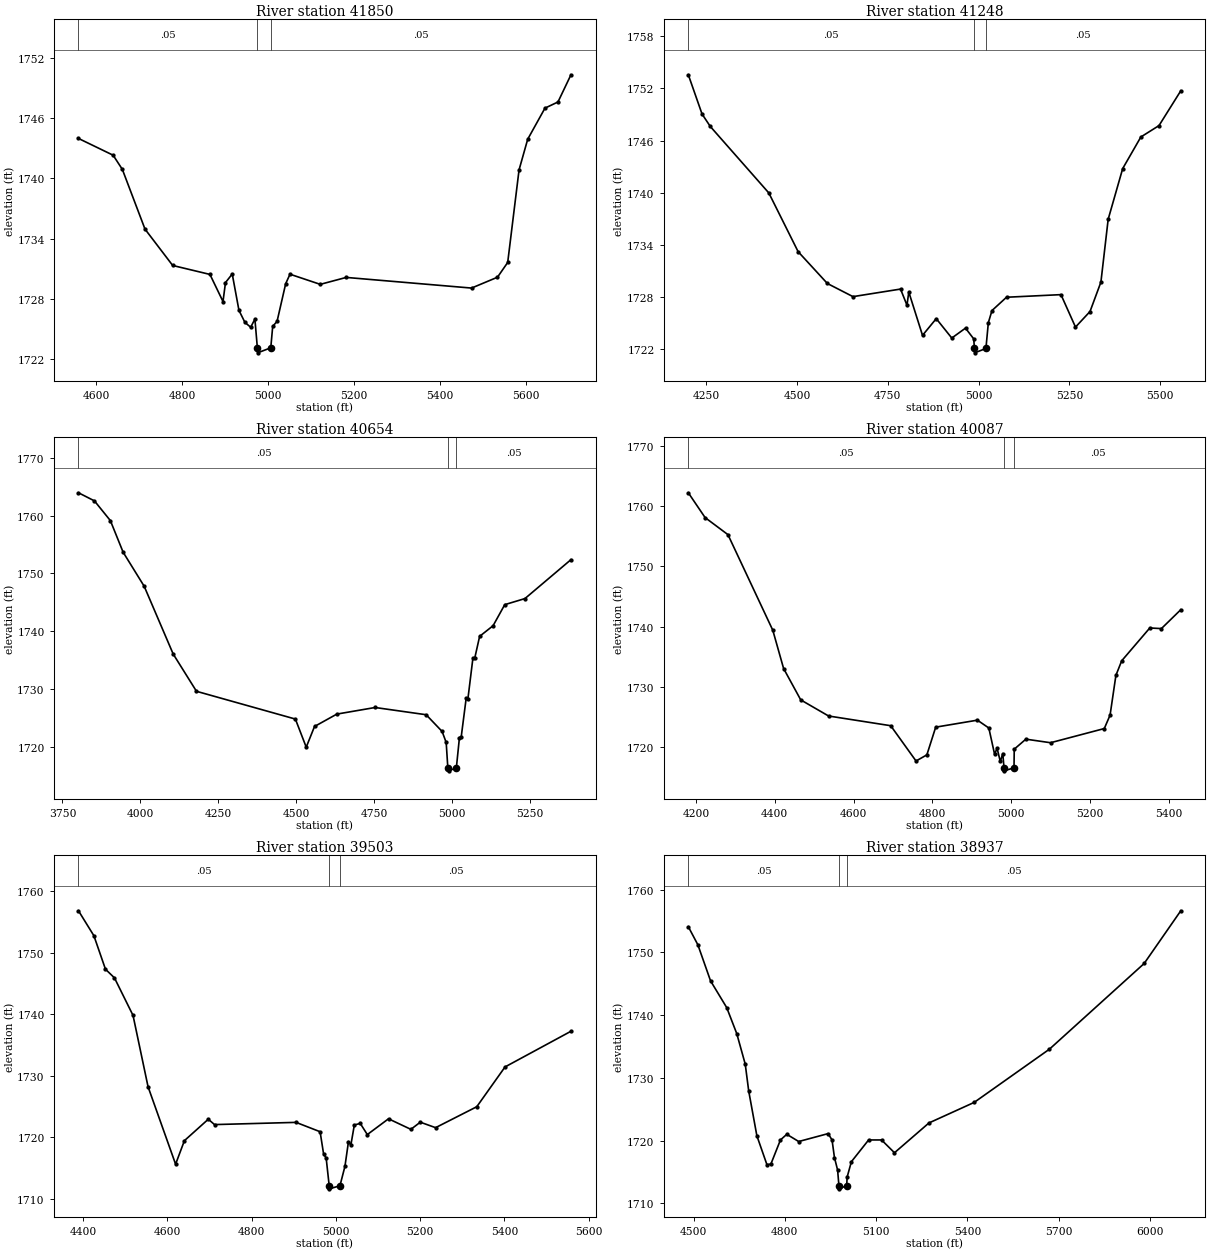
Type RM Length L Ch R = 1,41850,602,602,602
BEGIN DESCRIPTION:
Long Creek 67.0
END DESCRIPTION:
XS GIS Cut Line= 3
      1651541.67      6924454.77      1651328.35      6924815.78
      1651255.00      6925538.04
#Sta/Elev= 30
  4558.7 1743.97  4639.3 1742.30  4660.7 1740.89  4713.4 1734.94  4777.8 1731.32
  4864.4 1730.43  4894.8 1727.73  4900.6 1729.62  4916.3 1730.47  4931.9 1726.85
  4945.8 1725.65  4959.2 1725.17  4969.0 1725.98  4974.7 1723.12  4975.2 1722.62
  5005.9 1723.12  5010.4 1725.26  5020.5 1725.75  5040.6 1729.51  5050.6 1730.45
  5121.0 1729.44  5181.3 1730.13  5472.8 1729.07  5533.1 1730.15  5556.9 1731.62
  5583.3 1740.84  5603.4 1743.89  5643.6 1746.99  5673.8 1747.60  5704.0 1750.31
#Mann=3,-1,0
  4558.7    0.05       0  4974.7    0.03       0  5005.9    0.05       0
Bank Sta=4974.7,5005.9
Exp/Cntr=0.3,0.1

Type RM Length L Ch R = 1,41248,594,594,594
BEGIN DESCRIPTION:
Long Creek 66.0
END DESCRIPTION:
XS GIS Cut Line= 3
      1650855.00      6924187.96      1650755.00      6924988.00
      1650755.00      6925538.04
#Sta/Elev= 30
  4200.5 1753.57  4238.3 1749.06  4261.0 1747.63  4422.2 1739.99  4502.9 1733.24
  4583.5 1729.58  4654.0 1728.07  4785.0 1728.94  4802.7 1727.08  4807.7 1728.60
  4845.5 1723.62  4883.3 1725.54  4926.1 1723.31  4963.9 1724.45  4986.6 1723.21
  4988.4 1722.11  4988.9 1721.61  5020.1 1722.11  5026.8 1725.08  5036.8 1726.47
  5076.8 1728.00  5226.8 1728.30  5266.8 1724.57  5306.8 1726.36  5336.8 1729.74
  5356.8 1736.96  5396.8 1742.79  5446.8 1746.42  5496.8 1747.73  5556.8 1751.73
#Mann=3,-1,0
  4200.5    0.05       0  4988.4    0.05       0  5020.1    0.05       0
Bank Sta=4988.4,5020.1
Exp/Cntr=0.3,0.1

Type RM Length L Ch R = 1,40654,567,567,567
BEGIN DESCRIPTION:
Long Creek 65.0
END DESCRIPTION:
XS GIS Cut Line= 3
      1650055.00      6924088.02      1650305.00      6925238.00
      1650505.02      6925588.04
#Sta/Elev= 30
  3801.5 1763.94  3852.7 1762.54  3903.8 1759.13  3944.8 1753.66  4012.3 1747.78
  4105.4 1736.06  4180.1 1729.62  4497.4 1724.82  4532.2 1719.96  4558.8 1723.54
  4630.4 1725.68  4753.2 1726.82  4916.9 1725.57  4968.1 1722.68  4981.2 1720.78
  4986.3 1716.53  4988.4 1716.37  4988.8 1715.87  5013.8 1716.37  5023.7 1721.60
  5029.5 1721.77  5045.3 1728.40  5051.0 1728.36  5066.9 1735.33  5072.6 1735.30
  5088.5 1739.12  5131.7 1740.96  5169.1 1744.60  5233.9 1745.65  5381.5 1752.38
#Mann=3,-1,0
  3801.5    0.05       0  4988.4    0.05       0  5013.8    0.05       0
Bank Sta=4988.4,5013.8
Exp/Cntr=0.3,0.1

Type RM Length L Ch R = 1,40087,584,584,584
BEGIN DESCRIPTION:
Long Creek 64.0
END DESCRIPTION:
XS GIS Cut Line= 3
      1649305.02      6924438.02      1649805.00      6925088.00
      1650055.03      6925438.04
#Sta/Elev= 30
  4180.6 1762.17  4223.2 1758.06  4281.2 1755.23  4395.1 1739.38  4422.5 1733.04
  4466.0 1727.84  4536.7 1725.17  4694.4 1723.56  4758.7 1717.71  4786.2 1718.73
  4808.6 1723.32  4914.5 1724.48  4943.5 1723.18  4958.1 1718.83  4964.4 1719.83
  4972.6 1717.63  4978.9 1718.95  4982.0 1716.58  4982.4 1716.08  5007.4 1716.58
  5008.0 1719.67  5037.5 1721.33  5100.2 1720.74  5236.6 1723.09  5251.3 1725.32
  5266.1 1731.91  5280.8 1734.32  5352.1 1739.76  5381.6 1739.66  5430.8 1742.79
#Mann=3,-1,0
  4180.6    0.05       0  4982.0    0.05       0  5007.4    0.05       0
Bank Sta=4982,5007.4
Exp/Cntr=0.3,0.1

Type RM Length L Ch R = 1,39503,566,566,566
BEGIN DESCRIPTION:
Long Creek 63.0
END DESCRIPTION:
XS GIS Cut Line= 3
      1648955.00      6924788.00      1649305.00      6925288.00
      1649554.98      6925787.96
#Sta/Elev= 30
  4388.9 1756.80  4425.5 1752.75  4453.0 1747.31  4474.3 1745.91  4518.4 1739.82
  4554.1 1728.23  4619.5 1715.66  4640.4 1719.48  4697.1 1722.96  4711.9 1722.09
  4905.5 1722.45  4962.6 1720.93  4970.9 1717.32  4977.0 1716.66  4984.2 1712.16
  4984.6 1711.66  5009.7 1712.16  5021.6 1715.32  5030.0 1719.34  5035.6 1718.76
  5043.9 1722.03  5057.9 1722.28  5074.7 1720.47  5125.0 1723.03  5178.1 1721.32
  5200.5 1722.48  5236.8 1721.59  5334.6 1724.99  5401.7 1731.45  5558.2 1737.24
#Mann=3,-1,0
  4388.9    0.05       0  4984.2    0.05       0  5009.7    0.05       0
Bank Sta=4984.2,5009.7
Exp/Cntr=0.3,0.1

Type RM Length L Ch R = 1,38937,579,579,579
BEGIN DESCRIPTION:
Long Creek 62.0
END DESCRIPTION:
XS GIS Cut Line= 3
      1648655.00      6924988.00      1648805.00      6925488.00
      1649555.00      6926288.00
#Sta/Elev= 30
  4482.9 1754.07  4514.2 1751.20  4556.0 1745.44  4609.1 1741.18  4642.1 1737.04
  4670.0 1732.17  4681.3 1727.92  4708.2 1720.76  4741.3 1716.15  4754.3 1716.25
  4785.7 1720.09  4806.5 1720.99  4845.7 1719.84  4942.3 1721.10  4955.3 1720.09
  4963.2 1717.29  4973.6 1715.29  4977.9 1712.80  4978.3 1712.30  5003.4 1712.80
  5004.9 1714.17  5018.8 1716.62  5075.5 1720.09  5118.0 1720.09  5160.5 1718.05
  5273.8 1722.80  5422.3 1726.07  5669.9 1734.56  5981.1 1748.21  6101.5 1756.61
#Mann=3,-1,0
  4482.9    0.05       0  4977.9    0.03       0  5003.4    0.05       0
Bank Sta=4977.9,5003.4
Exp/Cntr=0.3,0.1

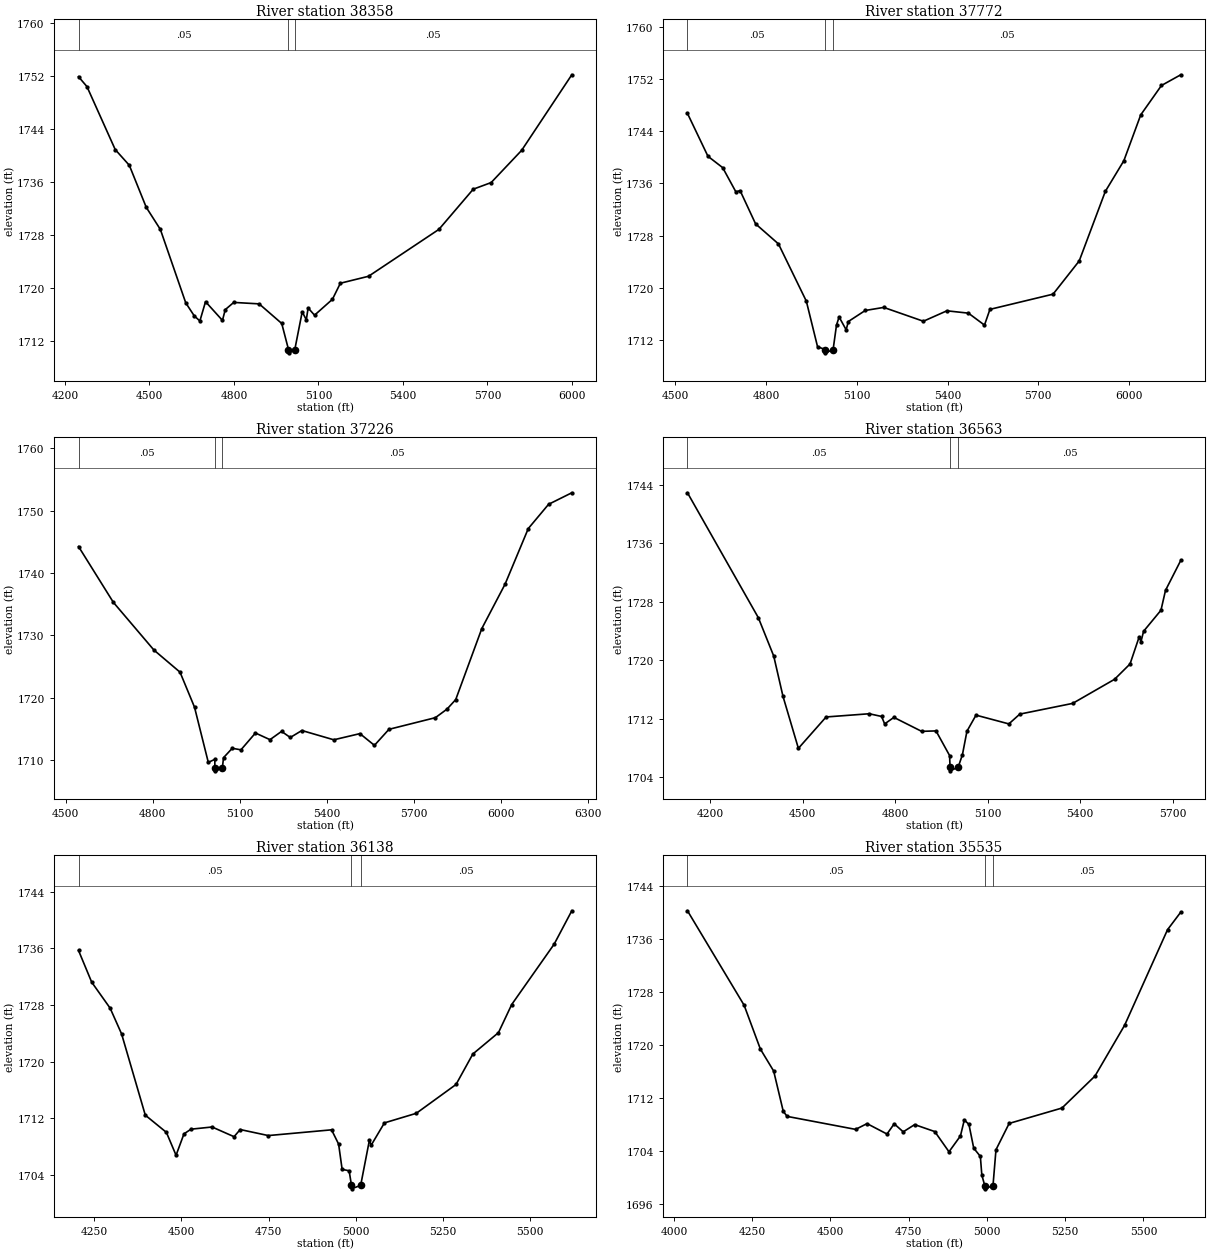
Type RM Length L Ch R = 1,38358,586,586,586
BEGIN DESCRIPTION:
Long Creek 61.0
END DESCRIPTION:
XS GIS Cut Line= 3
      1648355.00      6925088.03      1648405.00      6925838.00
      1649204.97      6926437.98
#Sta/Elev= 30
  4248.0 1751.93  4278.0 1750.43  4378.3 1740.92  4428.4 1738.54  4488.5 1732.19
  4538.6 1728.85  4628.8 1717.75  4658.9 1715.79  4678.9 1715.01  4699.0 1717.93
  4759.1 1715.10  4769.1 1716.73  4799.2 1717.82  4889.4 1717.60  4969.6 1714.64
  4993.6 1710.70  4994.0 1710.20  5016.0 1710.70  5042.3 1716.40  5056.9 1715.19
  5063.2 1716.98  5086.1 1715.89  5149.6 1718.29  5177.8 1720.72  5277.8 1721.77
  5527.8 1728.86  5649.6 1734.93  5713.2 1735.93  5821.5 1740.80  5999.6 1752.22
#Mann=3,-1,0
  4248.0    0.05       0  4993.6    0.03       0  5016.0    0.05       0
Bank Sta=4993.6,5016
Exp/Cntr=0.3,0.1

Type RM Length L Ch R = 1,37772,546,546,546
BEGIN DESCRIPTION:
Long Creek 60.0
END DESCRIPTION:
XS GIS Cut Line= 3
      1648104.99      6925138.04      1648005.00      6925588.00
      1647605.00      6926687.99
#Sta/Elev= 30
  4539.9 1746.71  4607.7 1740.14  4656.4 1738.40  4699.9 1734.70  4714.0 1734.88
  4765.2 1729.79  4840.8 1726.72  4933.0 1717.95  4970.1 1710.97  4995.8 1710.53
  4996.2 1710.03  5021.6 1710.53  5032.8 1714.29  5041.4 1715.52  5064.7 1713.56
  5072.0 1714.83  5127.9 1716.52  5189.0 1716.99  5320.1 1714.87  5397.9 1716.47
  5469.0 1716.11  5522.2 1714.28  5540.2 1716.69  5749.0 1719.02  5835.5 1724.11
  5921.9 1734.77  5983.1 1739.46  6039.0 1746.49  6107.5 1750.99  6171.3 1752.63
#Mann=3,-1,0
  4539.9    0.05       0  4995.8    0.03       0  5021.6    0.05       0
Bank Sta=4995.8,5021.6
Exp/Cntr=0.3,0.1

Type RM Length L Ch R = 1,37226,663,663,663
BEGIN DESCRIPTION:
Long Creek 59.0
END DESCRIPTION:
XS GIS Cut Line= 3
      1647505.00      6924988.01      1647505.00      6925438.00
      1647555.00      6926688.01
#Sta/Elev= 30
  4544.3 1744.27  4664.3 1735.32  4804.3 1727.66  4894.3 1724.11  4944.3 1718.49
  4991.8 1709.64  5014.3 1710.12  5014.5 1708.78  5015.0 1708.28  5040.4 1708.78
  5044.3 1710.39  5074.4 1711.90  5104.4 1711.65  5154.4 1714.35  5204.5 1713.28
  5244.5 1714.61  5274.5 1713.63  5314.5 1714.75  5424.6 1713.26  5514.7 1714.25
  5564.7 1712.37  5614.8 1714.94  5774.9 1716.81  5814.9 1718.18  5845.0 1719.71
  5935.0 1731.11  6015.1 1738.22  6095.2 1747.15  6165.2 1751.04  6245.3 1752.89
#Mann=3,-1,0
  4544.3    0.05       0  5014.5    0.03       0  5040.4    0.05       0
Bank Sta=5014.5,5040.4
Exp/Cntr=0.3,0.1

Type RM Length L Ch R = 1,36563,425,425,425
BEGIN DESCRIPTION:
Long Creek 58.0
END DESCRIPTION:
XS GIS Cut Line= 3
      1646955.00      6924938.01      1646963.16      6925732.03
      1647438.11      6926384.39
#Sta/Elev= 30
  4125.6 1742.94  4355.6 1725.83  4405.6 1720.57  4435.6 1715.06  4485.6 1707.93
  4575.6 1712.23  4715.6 1712.67  4755.6 1712.30  4765.6 1711.28  4795.6 1712.17
  4885.6 1710.26  4932.3 1710.32  4976.3 1706.95  4977.9 1705.35  4978.4 1704.85
  5004.2 1705.35  5018.0 1707.06  5032.7 1710.28  5062.1 1712.48  5168.7 1711.28
  5204.2 1712.62  5375.8 1714.09  5511.8 1717.39  5562.0 1719.49  5591.4 1723.17
  5597.5 1722.54  5606.0 1723.97  5662.4 1726.85  5677.1 1729.57  5726.6 1733.67
#Mann=3,-1,0
  4125.6    0.05       0  4977.9    0.03       0  5004.2    0.05       0
Bank Sta=4977.9,5004.2
Exp/Cntr=0.3,0.1

Type RM Length L Ch R = 1,36138,603,603,603
BEGIN DESCRIPTION:
Long Creek 57.0
END DESCRIPTION:
XS GIS Cut Line= 3
      1646705.01      6925037.96      1646605.00      6925838.00
      1646505.01      6926437.96
#Sta/Elev= 30
  4205.2 1735.72  4243.0 1731.24  4295.9 1727.57  4328.7 1723.94  4396.7 1712.47
  4457.2 1710.04  4484.9 1706.81  4507.6 1709.83  4527.7 1710.49  4588.2 1710.80
  4651.2 1709.43  4668.8 1710.44  4749.4 1709.59  4930.8 1710.40  4951.0 1708.39
  4961.1 1704.82  4981.2 1704.62  4987.9 1702.57  4988.3 1702.07  5014.3 1702.57
  5039.3 1708.93  5044.4 1708.23  5082.4 1711.38  5173.7 1712.73  5287.7 1716.80
  5335.9 1721.10  5409.4 1724.12  5447.4 1728.09  5569.1 1736.61  5619.7 1741.32
#Mann=3,-1,0
  4205.2    0.05       0  4987.9    0.05       0  5014.3    0.05       0
Bank Sta=4987.9,5014.3
Exp/Cntr=0.3,0.1

Type RM Length L Ch R = 1,35535,564,564,564
BEGIN DESCRIPTION:
Long Creek 56.0
END DESCRIPTION:
XS GIS Cut Line= 3
      1646555.00      6924938.00      1646055.00      6925738.00
      1645854.98      6926338.05
#Sta/Elev= 30
  4043.3 1740.24  4224.3 1725.99  4276.2 1719.38  4318.7 1716.06  4349.3 1709.99
  4361.7 1709.22  4580.4 1707.26  4617.0 1708.13  4680.7 1706.56  4703.7 1708.10
  4732.6 1706.89  4769.1 1707.98  4833.4 1706.93  4878.8 1703.88  4915.4 1706.27
  4927.7 1708.68  4942.5 1708.01  4957.8 1704.43  4979.0 1703.18  4983.7 1700.36
  4993.0 1698.79  4993.4 1698.29  5019.4 1698.79  5028.9 1704.19  5071.0 1708.16
  5239.7 1710.48  5345.1 1715.30  5440.0 1722.98  5577.0 1737.39  5619.2 1740.03
#Mann=3,-1,0
  4043.3    0.05       0  4993.0    0.03       0  5019.4    0.05       0
Bank Sta=4993,5019.4
Exp/Cntr=0.3,0.1

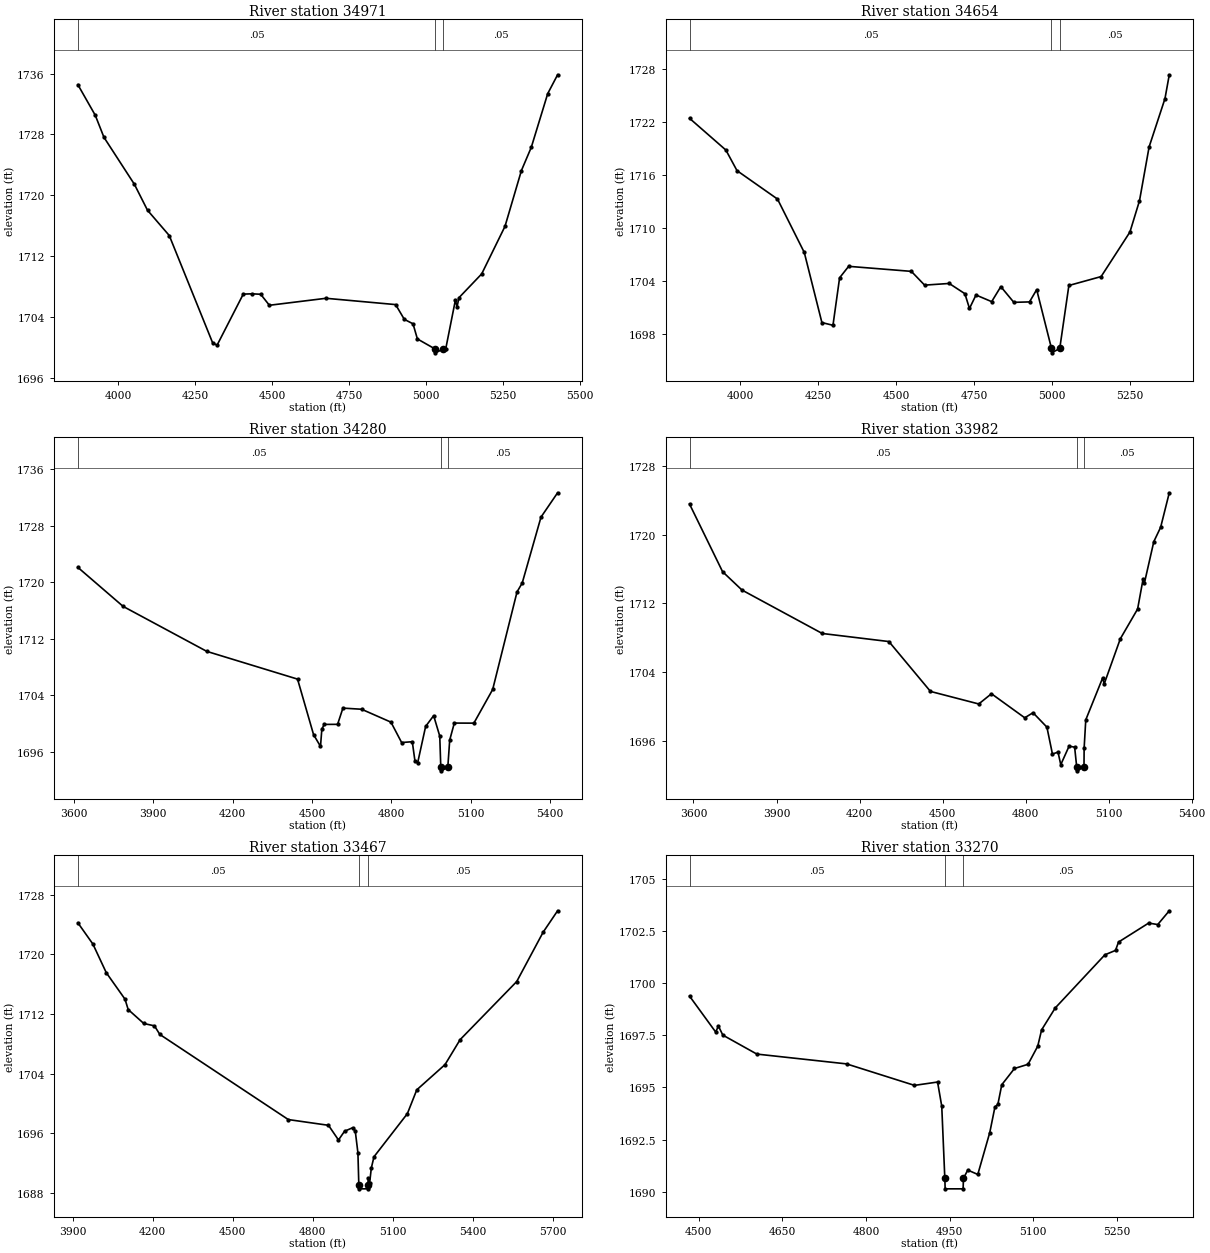
Type RM Length L Ch R = 1,34971,317,317,317
BEGIN DESCRIPTION:
Long Creek 55.0
END DESCRIPTION:
XS GIS Cut Line= 3
      1646304.99      6924888.01      1645505.00      6925688.00
      1645354.99      6926088.04
#Sta/Elev= 30
  3868.1 1734.56  3924.7 1730.53  3952.9 1727.63  4051.9 1721.44  4094.4 1718.03
  4165.1 1714.70  4306.5 1700.53  4320.6 1700.28  4405.5 1706.99  4433.8 1707.03
  4462.1 1706.97  4490.3 1705.52  4674.2 1706.44  4900.5 1705.61  4928.7 1703.67
  4957.0 1703.08  4971.2 1701.09  5029.0 1699.76  5029.5 1699.26  5055.5 1699.76
  5063.5 1699.83  5094.7 1706.21  5100.0 1705.31  5106.3 1706.52  5180.1 1709.65
  5255.8 1715.91  5309.2 1723.26  5341.2 1726.31  5394.6 1733.38  5426.7 1735.86
#Mann=3,-1,0
  3868.1    0.05       0  5029.0    0.03       0  5055.5    0.05       0
Bank Sta=5029,5055.5
Exp/Cntr=0.3,0.1

Type RM Length L Ch R = 1,34654,374,374,374
BEGIN DESCRIPTION:
Long Creek 54.0
END DESCRIPTION:
XS GIS Cut Line= 3
      1645929.31      6924599.70      1645242.80      6925540.57
      1645116.99      6925890.65
#Sta/Elev= 30
  3838.4 1722.44  3954.9 1718.84  3990.5 1716.51  4120.2 1713.29  4206.0 1707.24
  4262.4 1699.30  4297.9 1698.99  4319.1 1704.37  4348.1 1705.67  4548.9 1705.10
  4591.4 1703.54  4670.2 1703.73  4720.4 1702.57  4735.1 1700.90  4756.0 1702.42
  4806.2 1701.67  4835.5 1703.37  4877.2 1701.59  4927.4 1701.64  4950.4 1703.03
  4997.8 1696.37  4998.3 1695.87  5024.3 1696.37  5053.5 1703.50  5156.8 1704.51
  5249.0 1709.55  5279.7 1713.10  5310.5 1719.20  5361.3 1724.67  5375.1 1727.37
#Mann=3,-1,0
  3838.4    0.05       0  4997.8    0.03       0  5024.3    0.05       0
Bank Sta=4997.8,5024.3
Exp/Cntr=0.3,0.1

Type RM Length L Ch R = 1,34280,298,298,298
BEGIN DESCRIPTION:
Mapping XS 1f174a55
END DESCRIPTION:
XS GIS Cut Line= 3
      1645103.09      6924034.67      1644919.06      6925395.80
      1644842.67      6925829.81
#Sta/Elev= 30
  3614.9 1722.12  3786.0 1716.59  4102.6 1710.21  4445.7 1706.28  4506.3 1698.41
  4532.5 1696.74  4537.6 1699.19  4546.6 1699.86  4597.1 1699.87  4617.3 1702.17
  4687.9 1702.01  4798.9 1700.18  4839.3 1697.29  4879.6 1697.41  4889.7 1694.67
  4899.8 1694.40  4930.1 1699.58  4960.4 1701.10  4983.5 1698.20  4987.4 1693.78
  4987.9 1693.28  5013.9 1693.78  5021.1 1697.64  5038.5 1700.05  5112.5 1700.04
  5183.6 1704.81  5275.7 1718.64  5295.3 1719.90  5366.3 1729.24  5429.1 1732.69
#Mann=3,-1,0
  3614.9    0.05       0  4987.4    0.03       0  5013.9    0.05       0
Bank Sta=4987.4,5013.9
Exp/Cntr=0.3,0.1

Type RM Length L Ch R = 1,33982,515,515,515
BEGIN DESCRIPTION:
Long Creek 53.0
END DESCRIPTION:
XS GIS Cut Line= 3
      1644544.06      6923968.74      1644620.45      6925392.33
      1644705.01      6925688.04
#Sta/Elev= 30
  3585.7 1723.58  3705.1 1715.70  3775.2 1713.56  4065.2 1708.50  4306.0 1707.56
  4456.2 1701.75  4630.6 1700.29  4676.5 1701.48  4796.7 1698.68  4826.7 1699.27
  4876.8 1697.59  4896.8 1694.46  4916.9 1694.68  4926.9 1693.22  4956.9 1695.37
  4977.0 1695.26  4984.3 1693.00  4984.8 1692.50  5010.8 1693.00  5011.3 1695.14
  5017.2 1698.44  5078.4 1703.34  5083.6 1702.61  5142.0 1707.88  5204.5 1711.35
  5224.0 1714.79  5229.2 1714.40  5263.0 1719.20  5287.7 1720.87  5318.9 1724.89
#Mann=3,-1,0
  3585.7    0.05       0  4984.3    0.05       0  5010.8    0.05       0
Bank Sta=4984.3,5010.8
Exp/Cntr=0.3,0.1

Type RM Length L Ch R = 1,33467,197,197,197
BEGIN DESCRIPTION:
Mapping XS 301bb2bd
END DESCRIPTION:
XS GIS Cut Line= 3
      1644033.64      6924211.77      1644137.81      6925388.85
      1644570.91      6925828.88
#Sta/Elev= 30
  3919.3 1724.25  3975.8 1721.39  4025.9 1717.55  4096.2 1713.99  4108.1 1712.60
  4166.5 1710.73  4206.6 1710.41  4226.7 1709.26  4708.6 1697.83  4859.2 1697.06
  4896.7 1695.09  4919.4 1696.26  4949.5 1696.73  4959.6 1696.30  4969.6 1693.36
  4973.0 1689.03  4973.6 1688.53  5005.7 1688.53  5006.3 1689.03  5008.6 1689.92
  5013.6 1689.33  5019.8 1691.32  5029.9 1692.84  5155.0 1698.62  5190.3 1701.82
  5296.3 1705.21  5352.9 1708.56  5565.1 1716.36  5664.1 1722.98  5718.4 1725.86
#Mann=3,-1,0
  3919.3    0.05       0  4973.0    0.05       0  5006.3    0.05       0
Bank Sta=4973,5006.3
Exp/Cntr=0.3,0.1

Type RM Length L Ch R = 1,33270,564,564,564
BEGIN DESCRIPTION:
Mapping XS 91bb8bac
END DESCRIPTION:
XS GIS Cut Line= 4
      1643760.94      6924869.34      1643809.67      6925129.24
      1643919.33      6925267.33      1644073.67      6925657.23
#Sta/Elev= 30
  4483.8 1699.38  4530.6 1697.66  4535.7 1697.94  4543.5 1697.51  4604.5 1696.60
  4765.3 1696.13  4887.1 1695.10  4928.5 1695.26  4936.0 1694.10  4941.5 1690.64
  4942.1 1690.14  4974.3 1690.14  4974.9 1690.64  4982.6 1691.04  5000.6 1690.83
  5022.1 1692.84  5031.3 1694.06  5036.6 1694.19  5043.6 1695.13  5066.4 1695.91
  5090.7 1696.11  5108.1 1696.98  5115.0 1697.76  5139.4 1698.81  5228.5 1701.36
  5247.5 1701.57  5252.9 1701.97  5306.9 1702.88  5323.2 1702.81  5343.9 1703.47
#Mann=3,-1,0
  4483.8    0.05       0  4941.5    0.03       0  4974.9    0.05       0
Bank Sta=4941.5,4974.9
Exp/Cntr=0.3,0.1

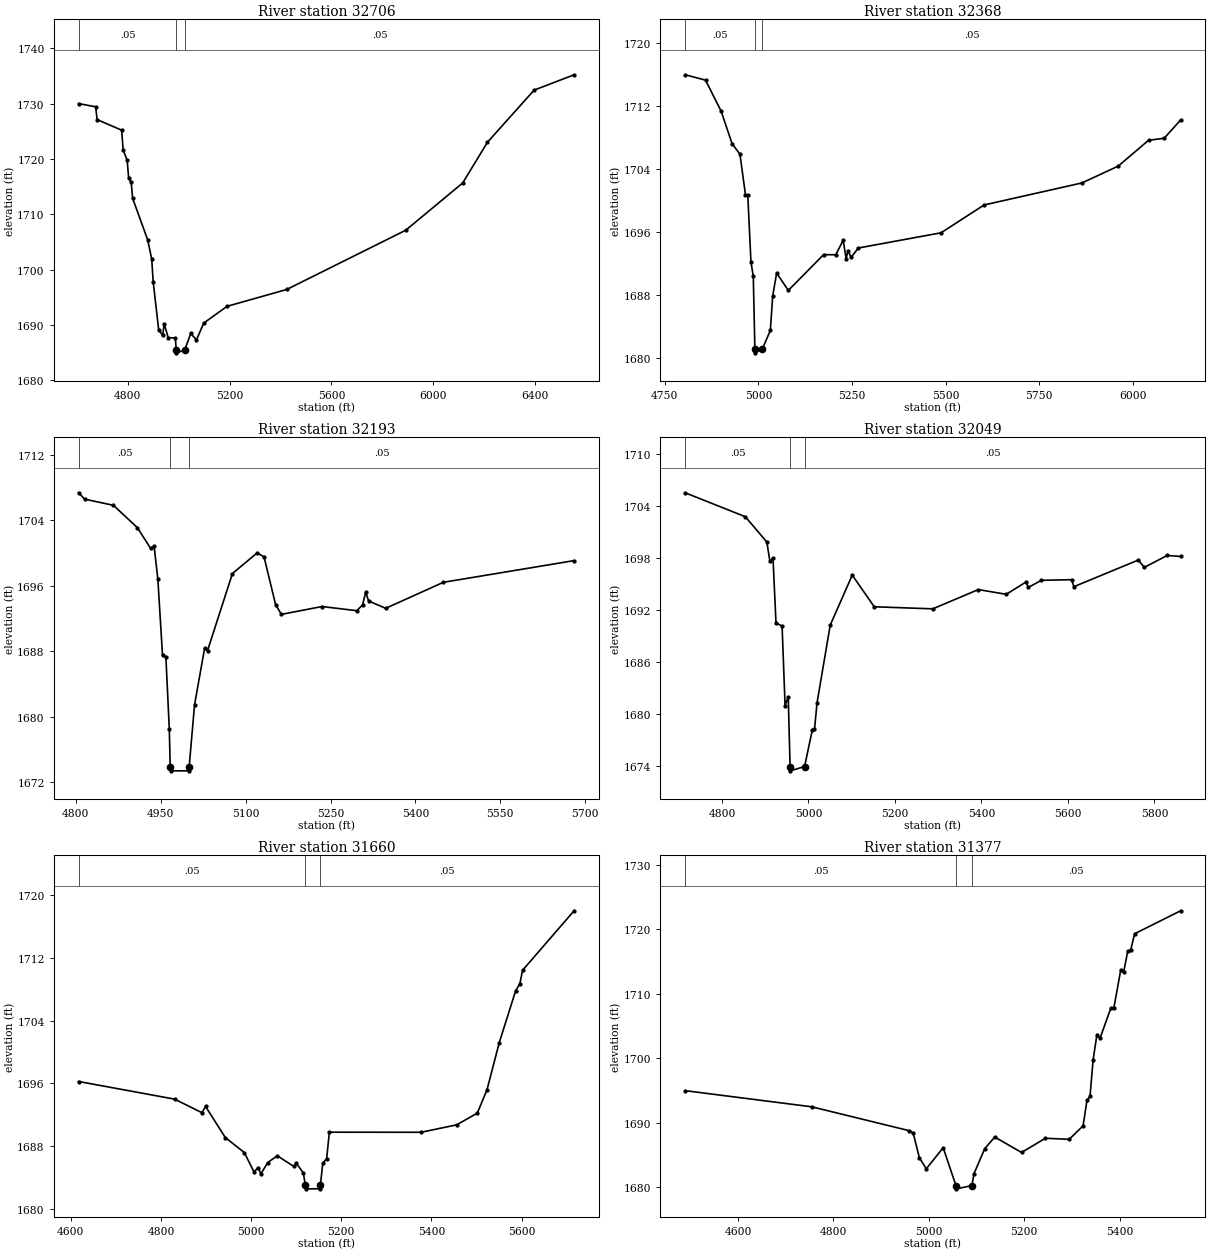
Type RM Length L Ch R = 1,32706,338,338,338
BEGIN DESCRIPTION:
Long Creek 52.0
END DESCRIPTION:
XS GIS Cut Line= 3
      1643205.01      6925038.01      1643405.00      6925388.00
      1644804.97      6926037.99
#Sta/Elev= 30
  4606.8 1730.01  4673.7 1729.43  4679.5 1727.12  4775.9 1725.20  4781.7 1721.64
  4797.5 1719.75  4803.3 1716.56  4813.4 1715.76  4819.1 1712.86  4878.2 1705.35
  4894.0 1701.88  4899.8 1697.74  4921.4 1689.06  4937.2 1688.10  4943.0 1690.19
  4958.8 1687.68  4986.9 1687.60  4990.3 1685.43  4990.9 1684.93  5023.8 1685.43
  5047.0 1688.43  5069.9 1687.28  5098.3 1690.31  5189.9 1693.34  5424.4 1696.39
  5891.9 1707.10  6116.0 1715.66  6213.1 1723.02  6396.3 1732.44  6553.4 1735.22
#Mann=3,-1,0
  4606.8    0.05       0  4990.3    0.03       0  5023.8    0.05       0
Bank Sta=4990.3,5023.8
Exp/Cntr=0.3,0.1

Type RM Length L Ch R = 1,32368,175,175,175
BEGIN DESCRIPTION:
Mapping XS 77403b84
END DESCRIPTION:
XS GIS Cut Line= 3
      1643050.99      6925527.73      1643214.20      6925645.80
      1644287.12      6925972.19
#Sta/Elev= 30
  4804.5 1715.96  4858.7 1715.28  4900.4 1711.34  4929.8 1707.19  4950.7 1705.86
  4965.4 1700.71  4971.6 1700.67  4980.1 1692.14  4986.3 1690.34  4990.5 1681.11
  4990.9 1680.61  5010.6 1681.11  5031.8 1683.46  5038.1 1687.83  5048.6 1690.75
  5079.9 1688.55  5174.0 1693.09  5206.5 1693.08  5226.3 1694.93  5234.2 1692.58
  5239.4 1693.61  5247.2 1692.75  5267.0 1693.94  5487.6 1695.87  5602.6 1699.41
  5863.9 1702.21  5960.8 1704.35  6041.6 1707.63  6083.4 1707.89  6127.4 1710.21
#Mann=3,-1,0
  4804.5    0.05       0  4990.5    0.03       0  5010.6    0.05       0
Bank Sta=4990.5,5010.6
Exp/Cntr=0.3,0.1

Type RM Length L Ch R = 1,32193,144,144,144
BEGIN DESCRIPTION:
Mapping XS 0b9533dd
END DESCRIPTION:
XS GIS Cut Line= 3
      1643039.46      6925718.12      1643173.26      6925809.67
      1643870.19      6925961.02
#Sta/Elev= 30
  4804.9 1707.38  4815.6 1706.60  4866.4 1705.85  4908.5 1703.13  4932.1 1700.59
  4938.2 1700.89  4944.9 1696.81  4953.1 1687.51  4959.1 1687.28  4965.1 1678.49
  4966.7 1673.90  4967.3 1673.40  4999.5 1673.40  5000.2 1673.90  5009.7 1681.47
  5027.5 1688.39  5032.6 1688.08  5076.6 1697.51  5120.6 1700.05  5132.5 1699.53
  5153.0 1693.69  5163.2 1692.52  5234.9 1693.48  5296.3 1692.97  5306.5 1693.67
  5312.1 1695.23  5317.2 1694.16  5347.4 1693.26  5449.3 1696.44  5680.2 1699.09
#Mann=3,-1,0
  4804.9    0.05       0  4966.7    0.03       0  5000.2    0.05       0
Bank Sta=4966.7,5000.2
Exp/Cntr=0.3,0.1

Type RM Length L Ch R = 1,32049,389,389,389
BEGIN DESCRIPTION:
Mapping XS 47455cc2
END DESCRIPTION:
XS GIS Cut Line= 3
      1643005.89      6925760.41      1643193.36      6925958.30
      1644051.32      6926118.60
#Sta/Elev= 30
  4715.1 1705.54  4854.2 1702.77  4903.9 1699.84  4910.8 1697.65  4918.1 1697.96
  4925.0 1690.50  4939.1 1690.12  4946.0 1680.94  4953.3 1681.94  4957.6 1673.89
  4958.2 1673.39  4991.1 1673.89  5009.0 1678.13  5014.0 1678.17  5019.9 1681.26
  5050.4 1690.24  5101.3 1696.02  5152.1 1692.36  5287.5 1692.12  5392.8 1694.35
  5457.3 1693.80  5503.2 1695.23  5508.3 1694.60  5538.7 1695.42  5608.5 1695.49
  5613.6 1694.68  5762.5 1697.76  5776.7 1696.92  5829.3 1698.29  5860.5 1698.18
#Mann=3,-1,0
  4715.1    0.05       0  4957.6    0.03       0  4991.1    0.05       0
Bank Sta=4957.6,4991.1
Exp/Cntr=0.3,0.1

Type RM Length L Ch R = 1,31660,283,283,283
BEGIN DESCRIPTION:
Mapping XS 76eab61b
END DESCRIPTION:
XS GIS Cut Line= 3
      1642991.97      6925996.48      1643020.37      6926259.18
      1643726.67      6926703.94
#Sta/Elev= 30
  4617.4 1696.22  4830.2 1693.97  4890.9 1692.24  4898.9 1693.04  4942.7 1689.07
  4985.1 1687.14  5006.3 1684.68  5015.7 1685.24  5021.6 1684.42  5036.9 1685.88
  5058.1 1686.74  5094.6 1685.38  5100.5 1685.77  5115.8 1684.55  5120.2 1683.02
  5120.8 1682.52  5153.1 1682.52  5153.7 1683.02  5158.9 1685.77  5167.6 1686.39
  5173.5 1689.75  5377.1 1689.74  5456.0 1690.69  5501.6 1692.18  5523.1 1695.15
  5550.2 1701.15  5586.7 1707.80  5596.1 1708.70  5602.0 1710.41  5716.3 1718.01
#Mann=3,-1,0
  4617.4    0.05       0  5120.2    0.05       0  5153.7    0.05       0
Bank Sta=5120.2,5153.7
Exp/Cntr=0.3,0.1

Type RM Length L Ch R = 1,31377,210,210,210
BEGIN DESCRIPTION:
Mapping XS 695ce580
END DESCRIPTION:
XS GIS Cut Line= 3
      1642964.18      6926065.98      1642856.56      6926430.52
      1643255.17      6926953.92
#Sta/Elev= 30
  4489.6 1694.99  4754.6 1692.49  4959.3 1688.78  4967.1 1688.46  4980.2 1684.59
  4994.7 1682.88  5030.1 1686.14  5056.9 1680.27  5057.5 1679.77  5090.4 1680.27
  5094.5 1682.10  5117.3 1686.02  5138.1 1687.80  5194.3 1685.41  5244.2 1687.61
  5294.1 1687.45  5323.2 1689.54  5331.4 1693.53  5337.7 1694.10  5344.2 1699.75
  5352.2 1703.68  5358.5 1703.08  5381.3 1707.77  5387.6 1707.78  5402.1 1713.70
  5408.4 1713.45  5416.7 1716.60  5423.0 1716.81  5431.2 1719.32  5527.6 1722.88
#Mann=3,-1,0
  4489.6    0.05       0  5056.9    0.05       0  5090.4    0.05       0
Bank Sta=5056.9,5090.4
Exp/Cntr=0.3,0.1