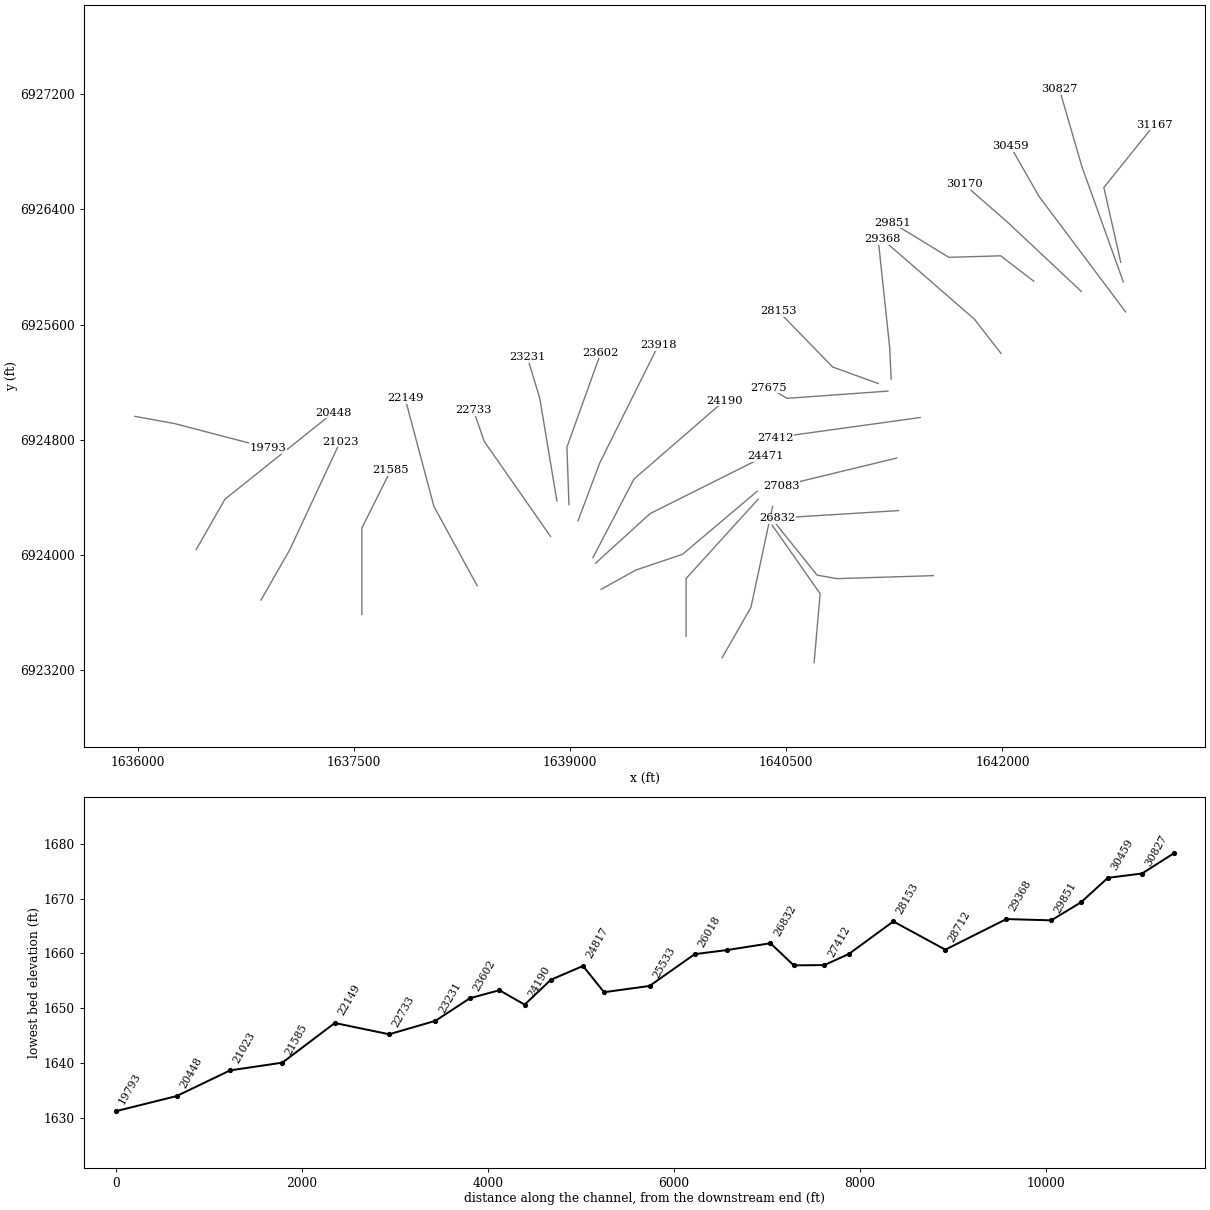
HEC-RAS study Long Creek.prj: Long Creek Base Level Engineering

--- Long Creek.g01 (geometry) --- (continued)

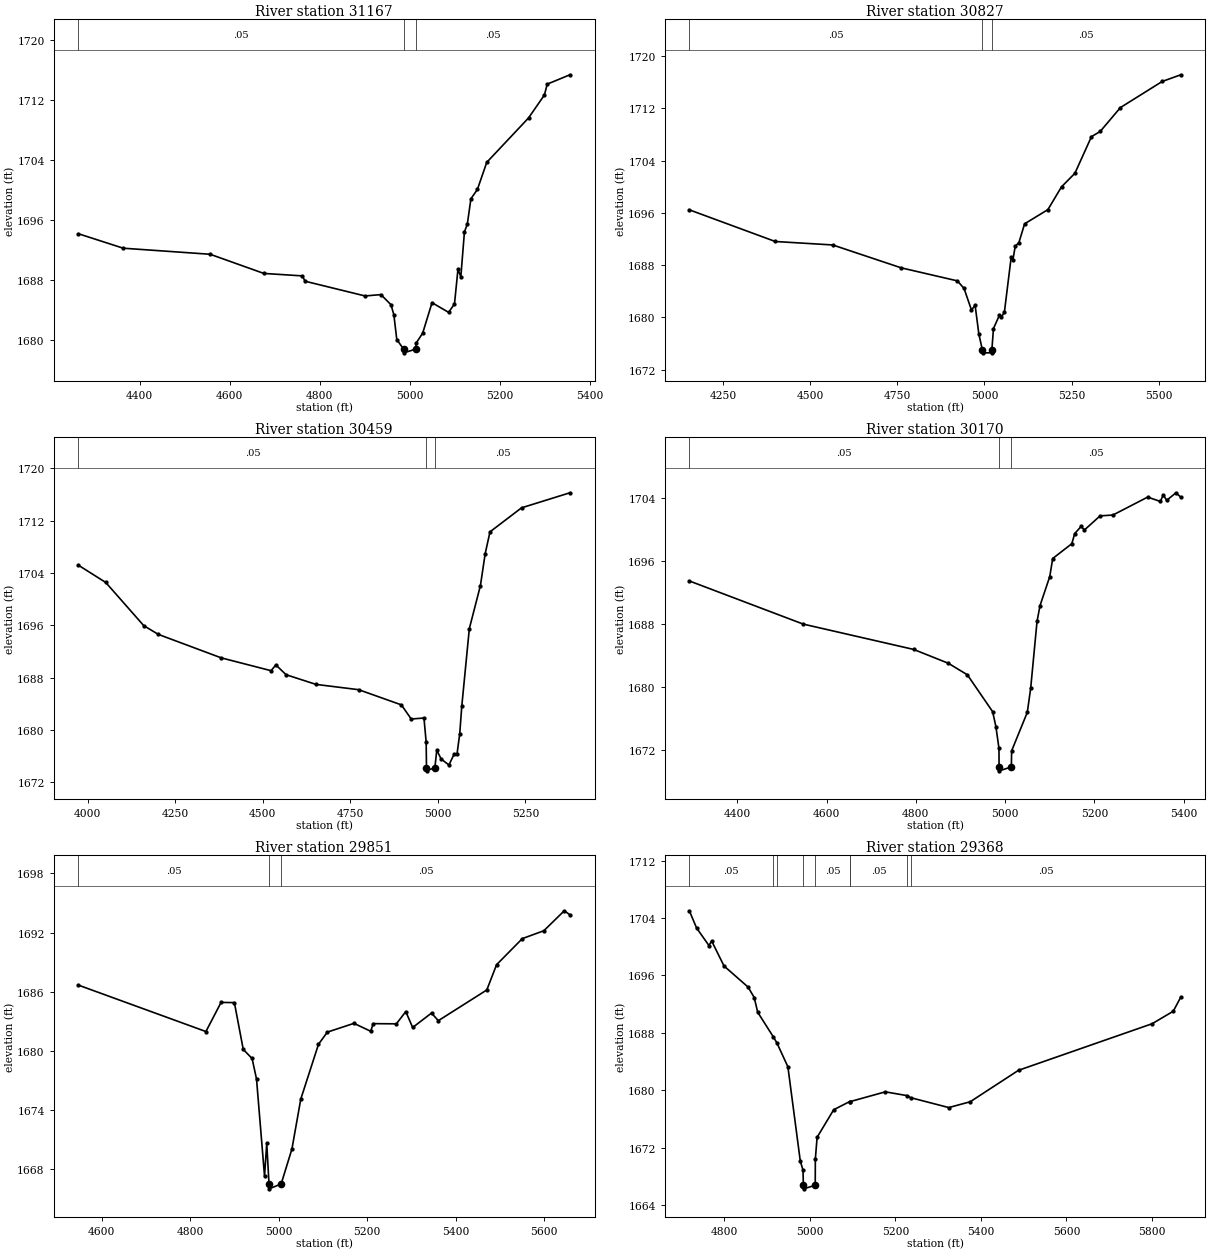
Type RM Length L Ch R = 1,31167,340,340,340
BEGIN DESCRIPTION:
Long Creek 51.0
END DESCRIPTION:
XS GIS Cut Line= 3
      1642821.16      6926032.58      1642703.97      6926550.84
      1643055.00      6926988.00
#Sta/Elev= 30
  4264.1 1694.14  4363.6 1692.21  4556.7 1691.40  4676.0 1688.84  4761.8 1688.51
  4767.5 1687.80  4900.9 1685.83  4936.1 1686.01  4958.5 1684.66  4964.9 1683.32
  4971.4 1680.01  4986.5 1678.73  4987.0 1678.23  5013.6 1678.73  5014.5 1679.54
  5028.9 1680.86  5049.7 1684.93  5086.5 1683.64  5099.6 1684.76  5107.3 1689.38
  5113.7 1688.40  5121.7 1694.39  5128.1 1695.42  5136.1 1698.81  5150.5 1700.06
  5171.3 1703.68  5264.1 1709.61  5299.3 1712.67  5305.7 1714.13  5356.1 1715.38
#Mann=3,-1,0
  4264.1    0.05       0  4986.5    0.05       0  5013.6    0.05       0
Bank Sta=4986.5,5013.6
Exp/Cntr=0.3,0.1

Type RM Length L Ch R = 1,30827,368,368,368
BEGIN DESCRIPTION:
Mapping XS f84d5abc
END DESCRIPTION:
XS GIS Cut Line= 3
      1642839.20      6925895.79      1642551.00      6926697.88
      1642395.20      6927234.52
#Sta/Elev= 30
  4152.8 1696.47  4399.5 1691.62  4564.4 1691.09  4760.8 1687.59  4922.4 1685.59
  4941.5 1684.43  4962.7 1681.14  4973.3 1681.84  4984.0 1677.44  4993.9 1675.07
  4994.5 1674.57  5020.8 1674.57  5021.4 1675.07  5026.0 1678.29  5043.1 1680.34
  5048.3 1680.01  5057.3 1680.79  5076.7 1689.17  5081.9 1688.84  5088.5 1690.91
  5098.9 1691.44  5115.4 1694.33  5182.2 1696.50  5221.3 1699.99  5259.8 1702.07
  5307.2 1707.67  5332.4 1708.47  5390.5 1712.13  5510.5 1716.13  5563.9 1717.15
#Mann=3,-1,0
  4152.8    0.05       0  4993.9    0.03       0  5021.4    0.05       0
Bank Sta=4993.9,5021.4
Exp/Cntr=0.3,0.1

Type RM Length L Ch R = 1,30459,289,289,289
BEGIN DESCRIPTION:
Long Creek 50.0
END DESCRIPTION:
XS GIS Cut Line= 3
      1642854.99      6925688.01      1642255.00      6926488.00
      1642055.00      6926838.00
#Sta/Elev= 30
  3973.9 1705.20  4052.0 1702.56  4160.3 1695.97  4202.0 1694.63  4381.2 1691.05
  4523.9 1689.08  4537.4 1689.97  4566.6 1688.47  4652.0 1686.99  4773.9 1686.18
  4895.8 1683.86  4923.9 1681.70  4960.3 1681.85  4966.6 1678.16  4967.5 1674.28
  4968.0 1673.78  4991.5 1674.28  4996.9 1676.95  5009.2 1675.60  5031.5 1674.67
  5046.6 1676.35  5054.5 1676.29  5062.4 1679.44  5068.2 1683.63  5089.8 1695.51
  5121.5 1702.10  5135.1 1706.98  5148.8 1710.30  5238.8 1713.97  5377.0 1716.27
#Mann=3,-1,0
  3973.9    0.05       0  4967.5    0.05       0  4991.5    0.05       0
Bank Sta=4967.5,4991.5
Exp/Cntr=0.3,0.1

Type RM Length L Ch R = 1,30170,319,319,319
BEGIN DESCRIPTION:
Mapping XS d13180ce
END DESCRIPTION:
XS GIS Cut Line= 3
      1642547.50      6925829.85      1642037.30      6926308.66
      1641735.00      6926572.91
#Sta/Elev= 30
  4292.6 1693.43  4547.7 1687.95  4795.3 1684.73  4873.0 1682.97  4915.5 1681.51
  4972.1 1676.83  4979.4 1674.94  4986.3 1672.18  4986.6 1669.81  4987.2 1669.31
  5014.1 1669.81  5014.7 1671.85  5049.8 1676.74  5057.4 1679.81  5071.6 1688.29
  5078.3 1690.30  5100.1 1693.98  5106.7 1696.28  5149.5 1698.16  5156.1 1699.45
  5170.3 1700.35  5177.9 1699.91  5213.0 1701.70  5241.5 1701.80  5319.4 1704.08
  5347.8 1703.53  5354.5 1704.36  5362.1 1703.67  5382.9 1704.63  5393.8 1704.06
#Mann=3,-1,0
  4292.6    0.05       0  4986.6    0.05       0  5014.1    0.05       0
Bank Sta=4986.6,5014.1
Exp/Cntr=0.3,0.1

Type RM Length L Ch R = 1,29851,483,483,483
BEGIN DESCRIPTION:
Mapping XS a1b6ccd7
END DESCRIPTION:
XS GIS Cut Line= 4
      1642217.59      6925900.93      1641987.82      6926076.89
      1641628.45      6926066.47      1641234.76      6926307.04
#Sta/Elev= 30
  4547.8 1686.67  4835.8 1681.97  4870.0 1684.92  4900.1 1684.90  4920.1 1680.16
  4940.1 1679.24  4950.1 1677.16  4968.2 1667.33  4973.2 1670.65  4978.3 1666.54
  4978.9 1666.04  5005.8 1666.54  5030.1 1670.08  5050.1 1675.13  5090.1 1680.68
  5110.1 1681.91  5170.2 1682.80  5207.9 1682.00  5213.8 1682.77  5266.0 1682.75
  5287.3 1683.99  5302.8 1682.38  5345.4 1683.84  5360.8 1683.07  5470.3 1686.18
  5492.4 1688.74  5550.5 1691.38  5599.2 1692.18  5645.3 1694.20  5658.1 1693.79
#Mann=3,-1,0
  4547.8    0.05       0  4978.3    0.05       0  5005.8    0.05       0
Bank Sta=4978.3,5005.8
Exp/Cntr=0.3,0.1

Type RM Length L Ch R = 1,29368,656,656,656
BEGIN DESCRIPTION:
Long Creek 48.0
END DESCRIPTION:
XS GIS Cut Line= 3
      1641990.44      6925399.79      1641805.00      6925638.00
      1641165.50      6926193.56
#Sta/Elev= 30
  4718.3 1705.00  4735.2 1702.61  4764.1 1700.16  4770.5 1700.79  4799.4 1697.31
  4855.5 1694.38  4870.0 1692.92  4878.1 1690.87  4914.5 1687.45  4922.9 1686.61
  4948.7 1683.27  4977.7 1670.13  4984.0 1668.88  4984.9 1666.77  4985.5 1666.27
  5012.6 1666.77  5012.9 1670.43  5017.0 1673.45  5055.8 1677.29  5093.3 1678.43
  5094.8 1678.43  5176.4 1679.78  5227.7 1679.25  5235.5 1678.97  5324.9 1677.59
  5374.9 1678.40  5487.8 1682.78  5800.3 1689.27  5849.6 1691.01  5867.3 1692.99
#Mann=9,-1,0
  4718.3    0.05       0  4914.5    0.12       0  4922.9    0.05       0
  4984.9    0.05       0  5012.6    0.05       0  5093.3    0.12       0
  5094.8    0.05       0  5227.7    0.12       0  5235.5    0.05       0
Bank Sta=4984.9,5012.6
Exp/Cntr=0.3,0.1

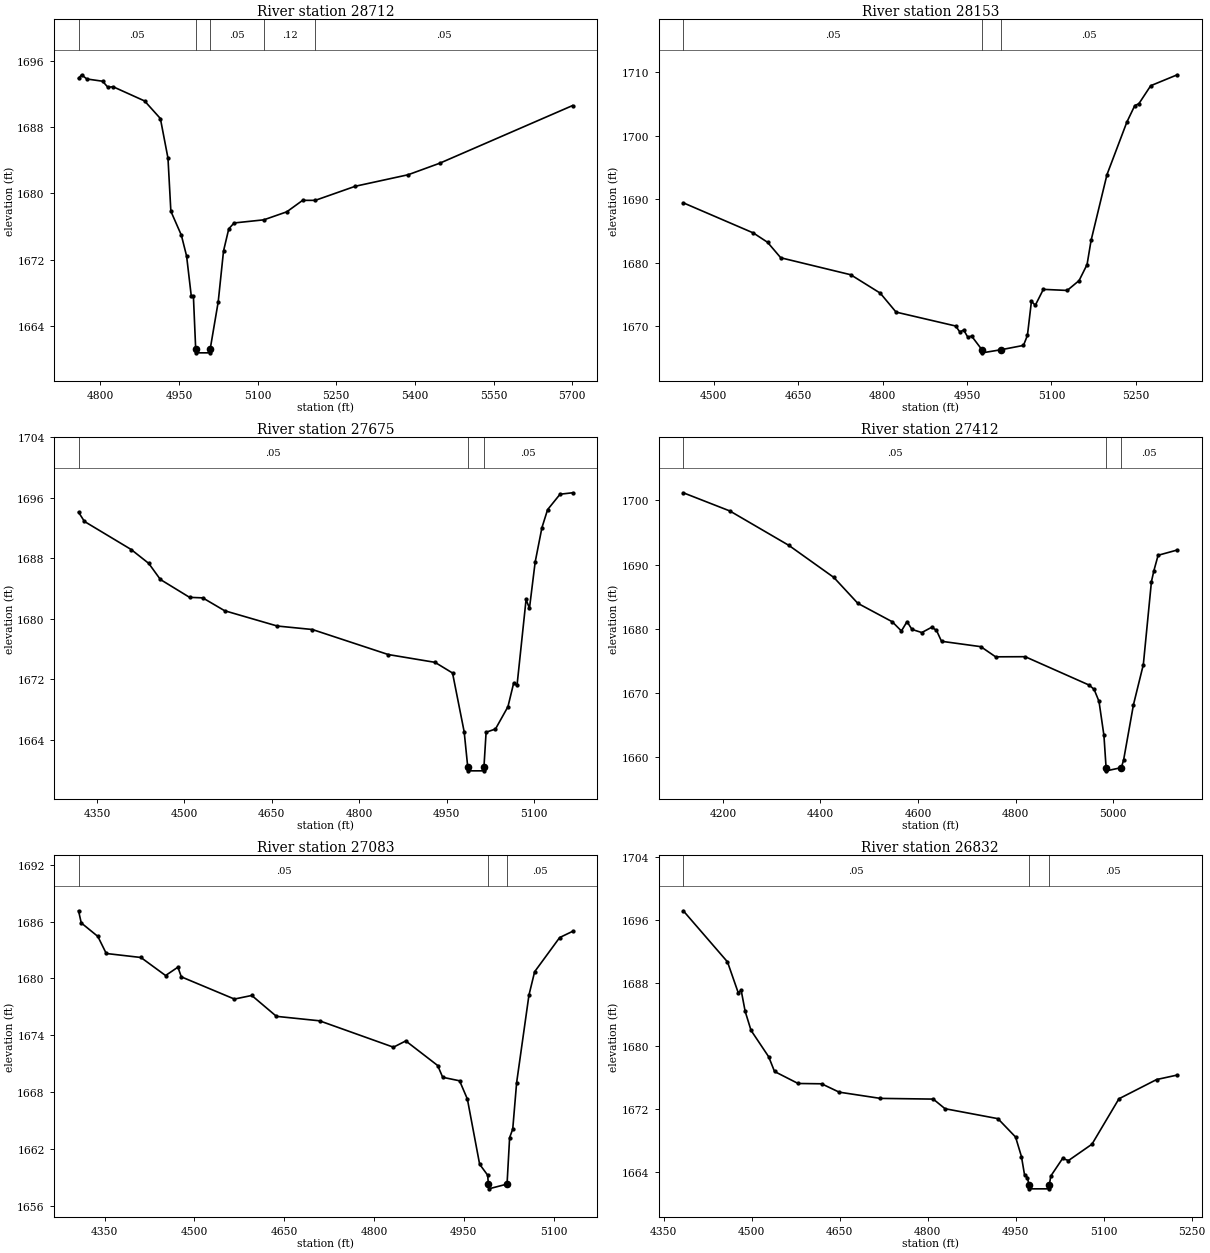
Type RM Length L Ch R = 1,28712,559,559,559
BEGIN DESCRIPTION:
Mapping XS d024ac69
END DESCRIPTION:
XS GIS Cut Line= 3
      1641228.08      6925222.21      1641217.67      6925440.94
      1641141.28      6926159.71
#Sta/Elev= 30
  4758.6 1693.96  4764.4 1694.38  4774.4 1693.87  4804.4 1693.60  4814.5 1692.87
  4824.5 1692.93  4884.5 1691.21  4914.6 1689.08  4929.1 1684.28  4934.6 1677.85
  4954.6 1674.95  4964.6 1672.42  4973.6 1667.53  4977.6 1667.53  4981.9 1661.20
  4982.5 1660.70  5009.0 1660.70  5009.7 1661.20  5024.9 1666.89  5035.0 1673.04
  5045.0 1675.72  5055.1 1676.43  5111.8 1676.81  5155.6 1677.78  5185.8 1679.17
  5209.9 1679.17  5286.4 1680.88  5386.9 1682.27  5447.3 1683.67  5700.4 1690.65
#Mann=5,-1,0
  4758.6    0.05       0  4981.9    0.05       0  5009.7    0.05       0
  5111.8    0.12       0  5209.9    0.05       0
Bank Sta=4981.9,5009.7
Exp/Cntr=0.3,0.1

Type RM Length L Ch R = 1,28153,478,478,478
BEGIN DESCRIPTION:
Mapping XS 14997923
END DESCRIPTION:
XS GIS Cut Line= 3
      1641137.85      6925190.92      1640821.84      6925305.52
      1640444.07      6925693.68
#Sta/Elev= 30
  4445.9 1689.45  4570.3 1684.71  4595.6 1683.24  4619.1 1680.80  4743.4 1678.13
  4795.8 1675.24  4824.0 1672.25  4930.0 1670.06  4937.2 1669.13  4944.2 1669.43
  4951.4 1668.32  4958.3 1668.47  4976.5 1666.34  4977.2 1665.84  5011.2 1666.34
  5050.4 1667.01  5057.4 1668.58  5064.5 1673.92  5071.5 1673.34  5085.7 1675.83
  5128.1 1675.66  5149.2 1677.21  5163.4 1679.73  5170.5 1683.52  5198.8 1693.89
  5234.1 1702.15  5248.2 1704.76  5255.4 1705.04  5276.5 1707.88  5323.7 1709.60
#Mann=3,-1,0
  4445.9    0.05       0  4976.5    0.03       0  5011.2    0.05       0
Bank Sta=4976.5,5011.2
Exp/Cntr=0.3,0.1

Type RM Length L Ch R = 1,27675,263,263,263
BEGIN DESCRIPTION:
Long Creek 46.0
END DESCRIPTION:
XS GIS Cut Line= 3
      1641205.05      6925138.00      1640505.00      6925088.00
      1640380.00      6925163.00
#Sta/Elev= 30
  4318.5 1694.09  4328.6 1692.87  4408.8 1689.16  4438.9 1687.33  4458.9 1685.20
  4509.0 1682.84  4531.6 1682.77  4569.2 1681.07  4659.4 1679.05  4719.6 1678.59
  4849.9 1675.28  4930.1 1674.25  4960.2 1672.84  4980.2 1665.06  4986.3 1660.41
  4986.9 1659.91  5013.5 1659.91  5014.1 1660.41  5017.8 1665.01  5033.9 1665.44
  5055.3 1668.39  5065.0 1671.48  5070.9 1671.23  5086.4 1682.56  5092.2 1681.39
  5102.0 1687.51  5113.6 1692.05  5123.3 1694.43  5144.7 1696.47  5166.1 1696.66
#Mann=3,-1,0
  4318.5    0.05       0  4986.3    0.05       0  5014.1    0.05       0
Bank Sta=4986.3,5014.1
Exp/Cntr=0.3,0.1

Type RM Length L Ch R = 1,27412,329,329,329
BEGIN DESCRIPTION:
Mapping XS 376e874d
END DESCRIPTION:
XS GIS Cut Line= 2
      1641429.47      6924954.82      1640426.04      6924815.94
#Sta/Elev= 30
  4118.7 1701.18  4214.1 1698.35  4335.2 1692.99  4427.4 1688.00  4476.6 1683.97
  4547.2 1681.10  4566.0 1679.66  4577.5 1681.12  4587.6 1679.91  4607.8 1679.42
  4628.0 1680.24  4637.8 1679.78  4648.2 1678.06  4728.9 1677.22  4759.2 1675.64
  4819.8 1675.66  4951.0 1671.24  4961.1 1670.58  4971.2 1668.70  4981.3 1663.40
  4985.7 1658.39  4986.4 1657.89  5017.0 1658.39  5021.7 1659.60  5041.9 1668.20
  5062.1 1674.43  5078.7 1687.34  5083.8 1689.07  5092.4 1691.45  5131.7 1692.27
#Mann=3,-1,0
  4118.7    0.05       0  4985.7    0.03       0  5017.0    0.05       0
Bank Sta=4985.7,5017
Exp/Cntr=0.3,0.1

Type RM Length L Ch R = 1,27083,251,251,251
BEGIN DESCRIPTION:
Mapping XS a59000e5
END DESCRIPTION:
XS GIS Cut Line= 2
      1641266.28      6924673.58      1640464.22      6924479.14
#Sta/Elev= 30
  4306.3 1687.13  4310.8 1685.85  4338.5 1684.43  4352.6 1682.63  4410.5 1682.21
  4451.7 1680.31  4472.3 1681.19  4478.0 1680.17  4566.7 1677.83  4595.7 1678.21
  4636.9 1676.01  4708.9 1675.54  4832.4 1672.76  4853.0 1673.42  4906.3 1670.83
  4914.7 1669.59  4942.9 1669.22  4955.9 1667.30  4976.4 1660.43  4989.9 1659.27
  4990.9 1658.34  4991.6 1657.84  5022.2 1658.34  5026.5 1663.24  5031.7 1664.13
  5038.2 1669.02  5058.8 1678.25  5068.3 1680.71  5110.1 1684.31  5131.6 1684.96
#Mann=3,-1,0
  4306.3    0.05       0  4990.9    0.03       0  5022.2    0.05       0
Bank Sta=4990.9,5022.2
Exp/Cntr=0.3,0.1

Type RM Length L Ch R = 1,26832,469,469,469
BEGIN DESCRIPTION:
Mapping XS 2cbc1f7a
END DESCRIPTION:
XS GIS Cut Line= 2
      1641280.20      6924308.99      1640439.92      6924256.91
#Sta/Elev= 30
  4383.5 1697.13  4458.8 1690.65  4477.1 1686.74  4482.1 1687.06  4488.9 1684.39
  4498.9 1681.97  4529.0 1678.62  4539.0 1676.75  4579.1 1675.23  4619.2 1675.19
  4649.2 1674.13  4719.3 1673.34  4809.5 1673.25  4829.6 1672.03  4919.7 1670.77
  4949.8 1668.44  4959.8 1665.97  4965.1 1663.64  4970.1 1663.30  4972.5 1662.37
  4973.2 1661.87  5006.5 1661.87  5007.3 1662.37  5009.9 1663.50  5029.9 1665.72
  5040.0 1665.46  5080.0 1667.53  5126.0 1673.29  5190.2 1675.73  5225.4 1676.30
#Mann=3,-1,0
  4383.5    0.05       0  4972.5    0.03       0  5007.3    0.05       0
Bank Sta=4972.5,5007.3
Exp/Cntr=0.3,0.1

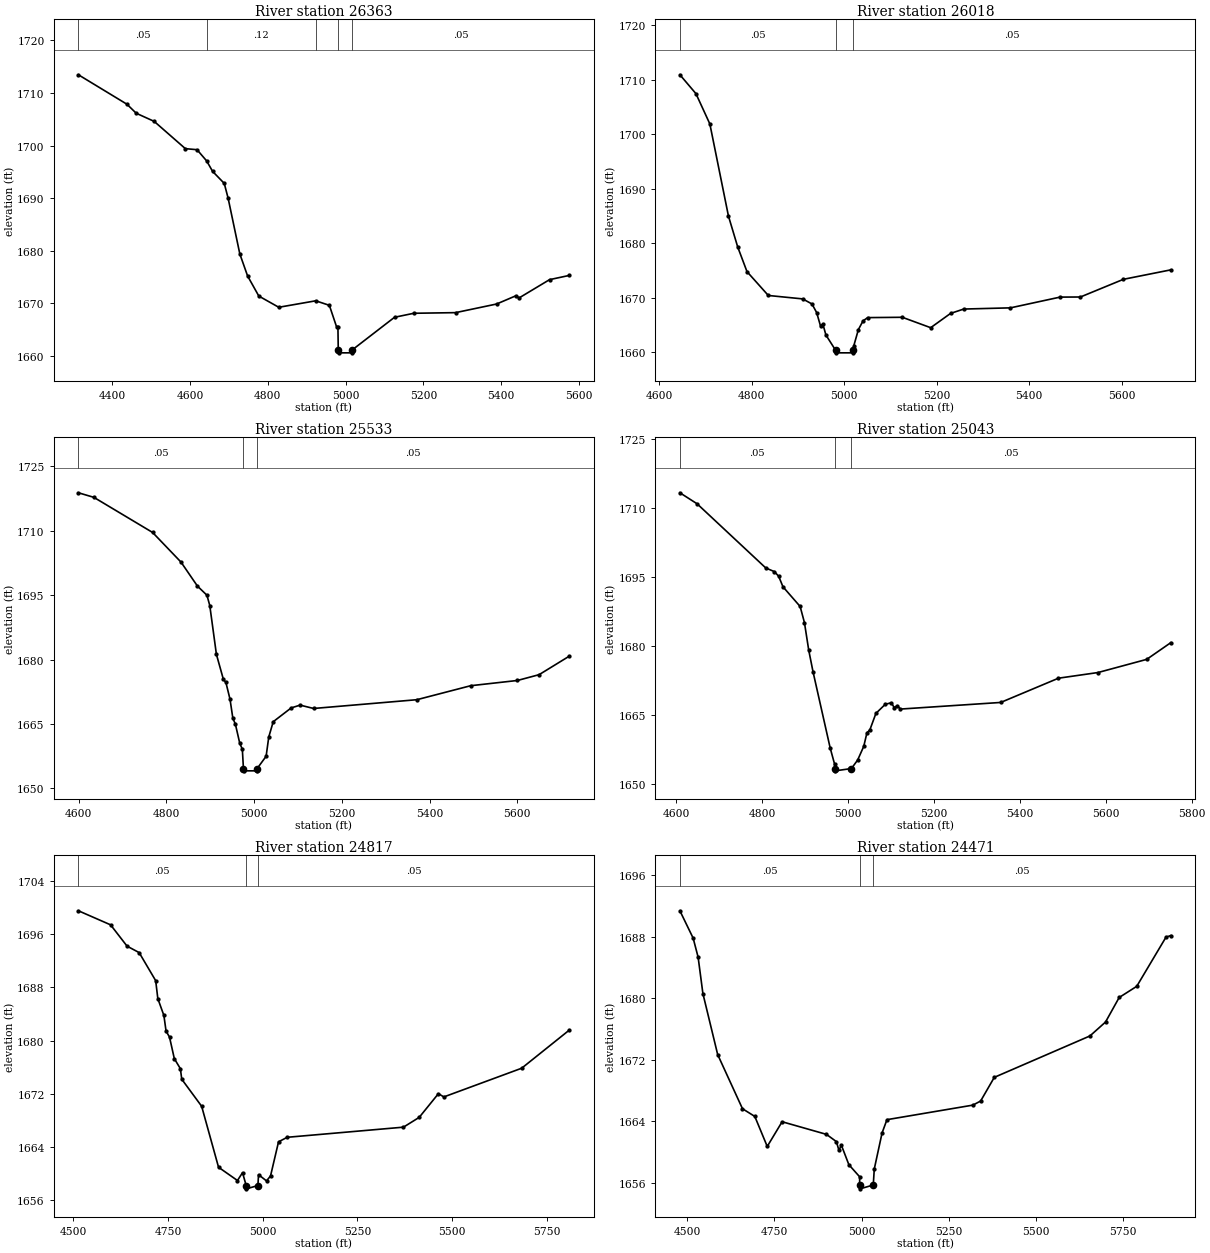
Type RM Length L Ch R = 1,26363,345,345,345
BEGIN DESCRIPTION:
Mapping XS 0a521c33
END DESCRIPTION:
XS GIS Cut Line= 4
      1641519.72      6923857.60      1640853.09      6923836.77
      1640714.20      6923861.08      1640429.71      6924214.94
#Sta/Elev= 30
  4313.3 1713.47  4438.1 1707.87  4461.9 1706.16  4508.1 1704.61  4588.2 1699.43
  4618.2 1699.23  4642.9 1697.10  4658.2 1695.11  4688.2 1692.82  4698.2 1689.98
  4728.2 1679.41  4748.2 1675.22  4777.0 1671.41  4828.3 1669.28  4923.3 1670.51
  4958.3 1669.65  4976.8 1665.57  4980.3 1665.57  4981.2 1661.12  4981.9 1660.62
  5015.3 1660.62  5016.1 1661.12  5125.8 1667.38  5175.4 1668.14  5282.6 1668.26
  5388.2 1669.90  5438.1 1671.48  5445.8 1671.05  5524.2 1674.53  5575.3 1675.34
#Mann=5,-1,0
  4313.3    0.05       0  4642.9    0.12       0  4923.3    0.05       0
  4981.2    0.03       0  5016.1    0.05       0
Bank Sta=4981.2,5016.1
Exp/Cntr=0.3,0.1

Type RM Length L Ch R = 1,26018,485,485,485
BEGIN DESCRIPTION:
Mapping XS 35447d89
END DESCRIPTION:
XS GIS Cut Line= 3
      1640693.36      6923253.43      1640735.03      6923732.60
      1640401.72      6924208.27
#Sta/Elev= 30
  4644.8 1710.87  4679.5 1707.41  4709.6 1701.85  4749.8 1684.96  4769.8 1679.30
  4789.9 1674.77  4836.0 1670.40  4910.4 1669.77  4930.4 1668.84  4940.5 1667.27
  4948.9 1664.80  4953.9 1665.18  4960.6 1663.14  4981.3 1660.38  4982.3 1659.88
  5019.1 1659.88  5020.1 1660.38  5020.8 1661.16  5030.8 1664.15  5040.9 1665.75
  5050.9 1666.34  5125.8 1666.40  5187.1 1664.49  5230.1 1667.11  5258.6 1667.91
  5359.7 1668.13  5466.9 1670.10  5510.9 1670.12  5603.8 1673.36  5706.6 1675.10
#Mann=3,-1,0
  4644.8    0.05       0  4981.3    0.03       0  5020.1    0.05       0
Bank Sta=4981.3,5020.1
Exp/Cntr=0.3,0.1

Type RM Length L Ch R = 1,25533,490,490,490
BEGIN DESCRIPTION:
Long Creek 45.0
END DESCRIPTION:
XS GIS Cut Line= 3
      1640055.02      6923288.03      1640255.00      6923638.00
      1640405.01      6924338.03
#Sta/Elev= 30
  4599.7 1718.83  4634.9 1717.77  4768.8 1709.59  4833.6 1702.68  4871.0 1697.10
  4892.6 1694.98  4899.1 1692.58  4914.2 1681.21  4930.1 1675.39  4935.8 1674.68
  4945.2 1670.77  4951.7 1666.32  4957.4 1664.98  4967.5 1660.47  4973.3 1659.13
  4975.8 1654.59  4976.6 1654.09  5006.0 1654.09  5006.8 1654.59  5027.5 1657.48
  5033.5 1661.96  5043.7 1665.53  5084.6 1668.74  5105.0 1669.39  5135.7 1668.61
  5370.9 1670.65  5493.7 1673.91  5600.2 1675.13  5649.6 1676.48  5718.7 1680.81
#Mann=3,-1,0
  4599.7    0.05       0  4975.8    0.05       0  5006.8    0.05       0
Bank Sta=4975.8,5006.8
Exp/Cntr=0.3,0.1

Type RM Length L Ch R = 1,25043,226,226,226
BEGIN DESCRIPTION:
Long Creek 44.0
END DESCRIPTION:
XS GIS Cut Line= 3
      1639805.00      6923437.99      1639805.00      6923838.00
      1640304.99      6924387.99
#Sta/Elev= 30
  4608.4 1713.37  4648.4 1710.98  4808.4 1697.03  4828.4 1696.24  4838.4 1695.23
  4848.4 1692.94  4888.4 1688.66  4898.4 1685.16  4908.4 1679.16  4918.4 1674.47
  4958.4 1657.89  4968.4 1654.48  4969.0 1653.45  4970.0 1652.95  5007.8 1653.45
  5022.3 1655.30  5036.5 1658.27  5043.9 1661.21  5050.6 1661.82  5064.8 1665.43
  5086.5 1667.40  5100.6 1667.75  5107.4 1666.70  5114.8 1667.12  5121.6 1666.37
  5355.4 1667.81  5489.9 1673.08  5581.8 1674.31  5695.3 1677.17  5751.7 1680.82
#Mann=3,-1,0
  4608.4    0.05       0  4969.0    0.05       0  5007.8    0.05       0
Bank Sta=4969,5007.8
Exp/Cntr=0.3,0.1

Type RM Length L Ch R = 1,24817,346,346,346
BEGIN DESCRIPTION:
Mapping XS ec379dd0
END DESCRIPTION:
XS GIS Cut Line= 4
      1639214.85      6923762.28      1639456.27      6923896.40
      1639779.85      6924005.38      1640297.88      6924442.94
#Sta/Elev= 30
  4513.7 1699.48  4598.6 1697.37  4642.1 1694.17  4674.0 1693.20  4717.6 1688.99
  4723.3 1686.29  4739.3 1683.76  4745.0 1681.41  4754.1 1680.52  4766.8 1677.28
  4782.8 1675.77  4786.4 1674.19  4838.9 1670.13  4883.5 1660.97  4933.4 1658.98
  4946.8 1660.16  4956.4 1658.23  4957.2 1657.73  4987.4 1658.23  4989.0 1659.86
  5010.1 1658.92  5020.7 1659.67  5041.8 1664.79  5064.7 1665.47  5371.4 1666.99
  5413.0 1668.46  5463.7 1672.02  5478.0 1671.53  5683.4 1675.84  5809.4 1681.58
#Mann=3,-1,0
  4513.7    0.05       0  4956.4    0.03       0  4987.4    0.05       0
Bank Sta=4956.4,4987.4
Exp/Cntr=0.3,0.1

Type RM Length L Ch R = 1,24471,281,281,281
BEGIN DESCRIPTION:
Long Creek 43.0
END DESCRIPTION:
XS GIS Cut Line= 3
      1639176.30      6923943.36      1639555.00      6924288.00
      1640355.02      6924688.01
#Sta/Elev= 30
  4479.7 1691.35  4517.7 1687.79  4531.9 1685.32  4545.6 1680.59  4588.0 1672.65
  4659.0 1665.62  4694.3 1664.62  4729.9 1660.72  4772.5 1663.93  4899.5 1662.29
  4927.9 1661.35  4935.3 1660.21  4942.1 1660.90  4963.7 1658.35  4994.5 1656.78
  4994.7 1655.71  4995.7 1655.21  5033.6 1655.71  5036.5 1657.79  5058.8 1662.47
  5072.8 1664.20  5318.8 1666.09  5341.1 1666.62  5380.3 1669.70  5654.2 1675.08
  5698.9 1676.89  5738.0 1680.08  5788.3 1681.53  5872.2 1687.93  5886.2 1688.13
#Mann=3,-1,0
  4479.7    0.05       0  4994.7    0.03       0  5033.6    0.05       0
Bank Sta=4994.7,5033.6
Exp/Cntr=0.3,0.1

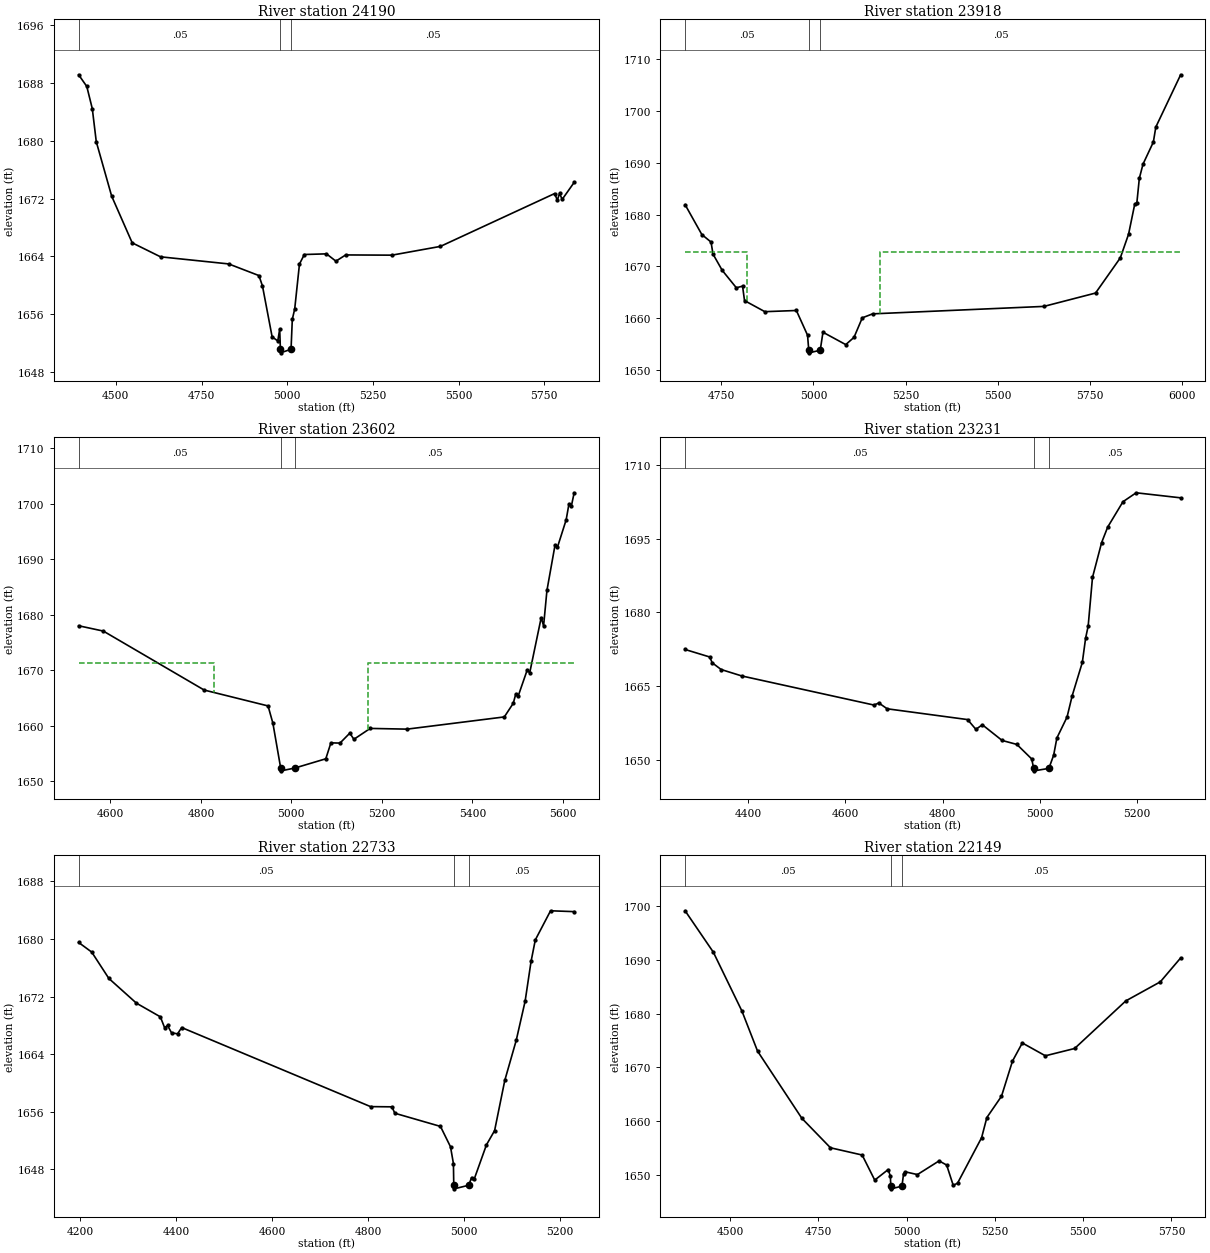
Type RM Length L Ch R = 1,24190,272,272,272
BEGIN DESCRIPTION:
Mapping XS 757373df
END DESCRIPTION:
XS GIS Cut Line= 3
      1639158.64      6923982.61      1639443.36      6924527.74
      1640070.88      6925072.05
#Sta/Elev= 30
  4391.4 1689.09  4415.2 1687.48  4431.3 1684.40  4442.9 1679.84  4487.7 1672.34
  4547.7 1665.88  4630.3 1663.95  4829.1 1662.97  4917.4 1661.36  4927.7 1659.93
  4955.9 1652.90  4972.4 1652.33  4978.0 1653.96  4980.0 1651.19  4980.8 1650.69
  5011.1 1651.19  5014.8 1655.32  5021.8 1656.75  5035.7 1662.96  5049.9 1664.27
  5114.5 1664.36  5142.0 1663.35  5170.5 1664.21  5305.4 1664.18  5446.9 1665.39
  5780.2 1672.69  5787.9 1671.76  5794.5 1672.71  5802.1 1671.88  5837.1 1674.23
#Mann=3,-1,0
  4391.4    0.05       0  4980.0    0.03       0  5011.1    0.05       0
Bank Sta=4980,5011.1
Exp/Cntr=0.3,0.1

Type RM Length L Ch R = 1,23918,316,316,316
BEGIN DESCRIPTION:
Long Creek 42.0
END DESCRIPTION:
XS GIS Cut Line= 3
      1639054.99      6924237.96      1639205.00      6924638.00
      1639613.49      6925458.28
#Sta/Elev= 30
  4652.0 1681.93  4697.4 1676.16  4722.3 1674.71  4727.7 1672.38  4752.6 1669.25
  4790.9 1665.88  4807.8 1666.19  4813.1 1663.40  4868.3 1661.26  4953.7 1661.49
  4984.0 1656.72  4987.3 1653.81  4988.1 1653.31  5018.4 1653.81  5025.8 1657.29
  5087.6 1654.90  5110.0 1656.30  5132.4 1660.07  5160.4 1660.84  5624.9 1662.28
  5764.9 1664.86  5832.0 1671.65  5854.4 1676.22  5871.2 1682.05  5876.8 1682.22
  5883.6 1687.02  5893.6 1689.76  5921.6 1694.02  5928.3 1696.92  5995.6 1707.02
#Mann=3,-1,0
  4652.0    0.05       0  4987.3    0.03       0  5018.4    0.05       0
#XS Ineff=2,0
    0.00 4819.80 1672.73 5180.20    0.00 1672.73
Permanent Ineff=
       F       F
Bank Sta=4987.3,5018.4
Exp/Cntr=0.3,0.1

Type RM Length L Ch R = 1,23602,371,371,371
BEGIN DESCRIPTION:
Mapping XS 8feca8df
END DESCRIPTION:
XS GIS Cut Line= 3
      1638991.97      6924350.63      1638978.09      6924749.96
      1639213.62      6925404.61
#Sta/Elev= 30
  4529.8 1677.99  4584.4 1677.03  4807.3 1666.41  4948.5 1663.55  4959.2 1660.43
  4976.4 1652.36  4977.2 1651.86  5007.5 1652.36  5076.1 1654.03  5087.4 1656.90
  5107.5 1656.86  5129.2 1658.65  5138.2 1657.54  5174.2 1659.50  5255.7 1659.37
  5470.7 1661.57  5490.5 1664.03  5496.1 1665.72  5501.4 1665.34  5521.5 1670.07
  5526.8 1669.50  5552.2 1679.45  5557.5 1677.97  5564.9 1684.35  5582.9 1692.57
  5588.2 1692.15  5607.4 1697.07  5613.6 1699.95  5618.9 1699.55  5625.1 1701.94
#Mann=3,-1,0
  4529.8    0.05       0  4976.4    0.03       0  5007.5    0.05       0
#XS Ineff=2,0
    0.00 4830.00 1671.28 5170.00    0.00 1671.28
Permanent Ineff=
       F       F
Bank Sta=4976.4,5007.5
Exp/Cntr=0.3,0.1

Type RM Length L Ch R = 1,23231,498,498,498
BEGIN DESCRIPTION:
Long Creek 41.0
END DESCRIPTION:
XS GIS Cut Line= 3
      1638908.65      6924374.92      1638789.79      6925087.77
      1638703.77      6925371.53
#Sta/Elev= 30
  4270.4 1672.46  4321.1 1670.93  4326.1 1669.75  4344.5 1668.38  4386.9 1667.07
  4658.8 1661.14  4668.9 1661.56  4686.0 1660.38  4851.4 1658.18  4868.4 1656.20
  4881.8 1657.12  4922.4 1653.93  4952.8 1653.12  4983.2 1650.17  4987.4 1648.24
  4988.2 1647.74  5018.6 1648.24  5028.4 1650.92  5035.1 1654.44  5056.0 1658.70
  5066.5 1663.02  5087.4 1669.83  5094.2 1674.80  5099.4 1677.22  5108.3 1687.13
  5127.1 1694.24  5139.6 1697.40  5171.0 1702.56  5198.1 1704.38  5289.6 1703.35
#Mann=3,-1,0
  4270.4    0.05       0  4987.4    0.03       0  5018.6    0.05       0
Bank Sta=4987.4,5018.6
Exp/Cntr=0.3,0.1

Type RM Length L Ch R = 1,22733,584,584,584
BEGIN DESCRIPTION:
Long Creek 40.0
END DESCRIPTION:
XS GIS Cut Line= 3
      1638864.64      6924129.26      1638405.00      6924788.00
      1638329.16      6925004.45
#Sta/Elev= 30
  4196.5 1679.51  4223.8 1678.17  4259.5 1674.51  4316.9 1671.08  4366.8 1669.18
  4375.6 1667.68  4381.7 1667.98  4390.1 1666.96  4402.6 1666.82  4411.3 1667.69
  4804.8 1656.71  4849.3 1656.68  4855.4 1655.79  4950.5 1653.96  4971.4 1651.13
  4977.5 1648.80  4978.2 1645.79  4979.0 1645.29  5009.4 1645.79  5015.3 1646.86
  5020.9 1646.66  5046.3 1651.40  5063.3 1653.38  5084.5 1660.35  5108.3 1665.90
  5126.9 1671.35  5139.3 1676.89  5148.1 1679.86  5179.9 1683.91  5229.1 1683.79
#Mann=3,-1,0
  4196.5    0.05       0  4978.2    0.03       0  5009.4    0.05       0
Bank Sta=4978.2,5009.4
Exp/Cntr=0.3,0.1

Type RM Length L Ch R = 1,22149,564,564,564
BEGIN DESCRIPTION:
Long Creek 39.0
END DESCRIPTION:
XS GIS Cut Line= 3
      1638355.02      6923787.97      1638055.00      6924338.00
      1637855.01      6925087.96
#Sta/Elev= 30
  4373.2 1699.15  4453.0 1691.45  4534.1 1680.46  4578.3 1673.00  4703.6 1660.49
  4784.7 1654.99  4874.4 1653.64  4910.0 1648.97  4948.0 1650.93  4954.2 1649.71
  4955.5 1647.84  4956.3 1647.34  4987.0 1647.84  4991.7 1650.17  4996.9 1650.50
  5030.8 1650.00  5092.2 1652.55  5113.6 1651.77  5132.3 1647.97  5144.6 1648.42
  5212.5 1656.87  5227.4 1660.63  5268.8 1664.59  5299.9 1671.14  5327.7 1674.52
  5393.0 1672.13  5475.8 1673.49  5620.7 1682.36  5718.4 1685.91  5775.9 1690.36
#Mann=3,-1,0
  4373.2    0.05       0  4955.5    0.03       0  4987.0    0.05       0
Bank Sta=4955.5,4987
Exp/Cntr=0.3,0.1

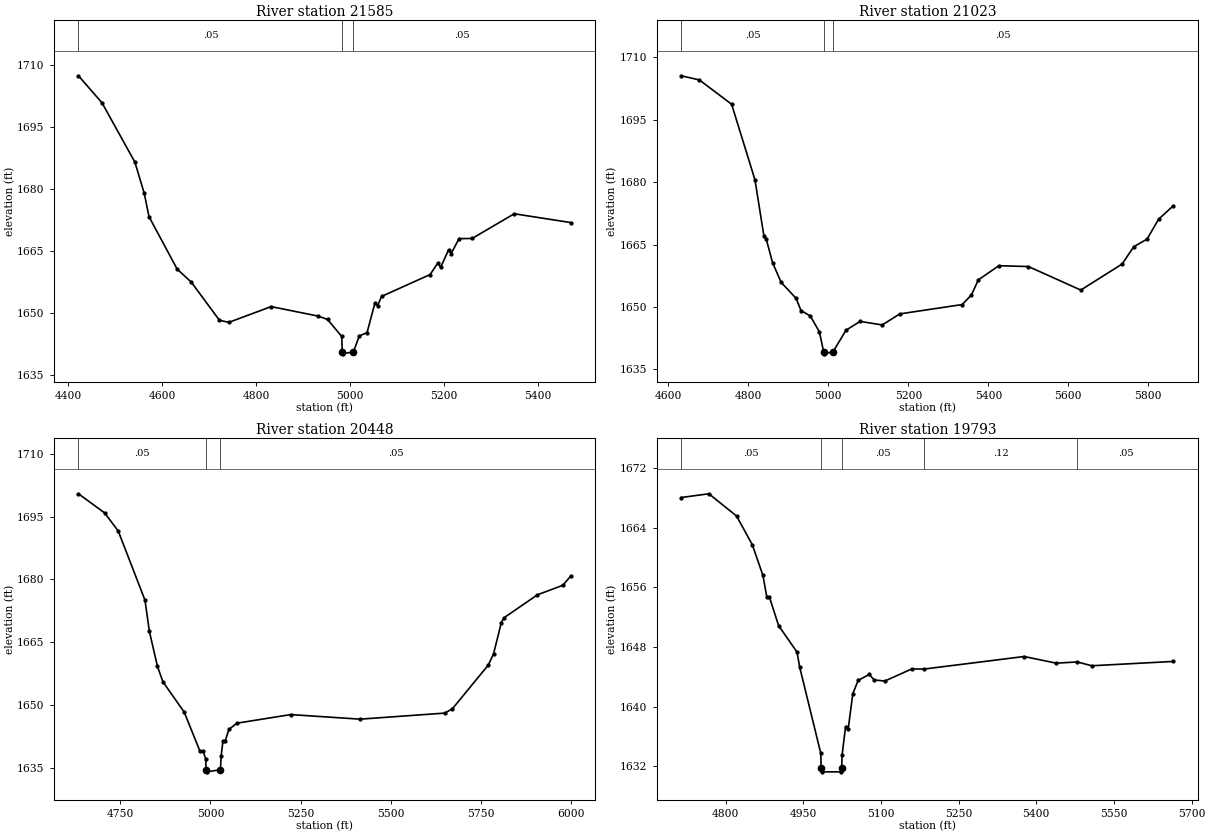
Type RM Length L Ch R = 1,21585,562,562,562
BEGIN DESCRIPTION:
Long Creek 38.0
END DESCRIPTION:
XS GIS Cut Line= 3
      1637555.00      6923587.97      1637555.00      6924188.00
      1637754.98      6924587.96
#Sta/Elev= 30
  4422.3 1707.30  4472.3 1700.78  4542.3 1686.45  4562.3 1678.88  4572.3 1673.28
  4632.3 1660.58  4662.3 1657.45  4722.3 1648.22  4742.3 1647.73  4832.3 1651.53
  4932.3 1649.24  4952.3 1648.42  4982.3 1644.33  4983.6 1640.62  4984.2 1640.12
  5007.3 1640.62  5019.8 1644.44  5036.3 1645.26  5053.1 1652.43  5058.7 1651.75
  5067.1 1653.99  5170.5 1659.28  5187.2 1662.12  5192.8 1661.00  5209.6 1665.21
  5215.2 1664.36  5232.0 1667.95  5259.9 1668.00  5349.4 1673.96  5469.5 1671.84
#Mann=3,-1,0
  4422.3    0.05       0  4983.6    0.03       0  5007.3    0.05       0
Bank Sta=4983.6,5007.3
Exp/Cntr=0.3,0.1

Type RM Length L Ch R = 1,21023,575,575,575
BEGIN DESCRIPTION:
Long Creek 37.0
END DESCRIPTION:
XS GIS Cut Line= 3
      1636855.01      6923688.02      1637055.00      6924038.00
      1637404.99      6924787.97
#Sta/Elev= 30
  4632.2 1705.60  4677.5 1704.60  4758.1 1698.75  4816.5 1680.56  4838.8 1667.08
  4844.5 1666.39  4860.4 1660.65  4882.0 1655.89  4919.4 1652.05  4931.6 1649.11
  4954.7 1647.83  4977.7 1643.97  4988.1 1639.21  4988.7 1638.71  5011.8 1639.21
  5044.0 1644.38  5079.4 1646.52  5134.6 1645.66  5178.7 1648.32  5334.8 1650.57
  5357.7 1652.88  5375.0 1656.50  5426.3 1659.91  5500.3 1659.71  5631.2 1654.05
  5734.5 1660.32  5763.6 1664.48  5796.7 1666.30  5825.9 1671.12  5862.9 1674.36
#Mann=3,-1,0
  4632.2    0.05       0  4988.1    0.03       0  5011.8    0.05       0
Bank Sta=4988.1,5011.8
Exp/Cntr=0.3,0.1

Type RM Length L Ch R = 1,20448,655,655,655
BEGIN DESCRIPTION:
Long Creek 36.0
END DESCRIPTION:
XS GIS Cut Line= 3
      1636404.99      6924037.99      1636605.00      6924388.00
      1637355.00      6924988.00
#Sta/Elev= 30
  4634.3 1700.43  4707.0 1695.85  4744.5 1691.53  4818.6 1675.01  4830.8 1667.55
  4853.1 1659.22  4868.3 1655.53  4927.3 1648.28  4970.5 1639.04  4979.8 1638.97
  4986.3 1637.21  4988.2 1634.53  4989.2 1634.03  5027.7 1634.53  5029.5 1637.77
  5034.5 1641.34  5040.6 1641.34  5051.0 1644.16  5073.4 1645.65  5222.3 1647.70
  5414.4 1646.61  5649.7 1648.06  5670.5 1649.12  5769.8 1659.54  5784.2 1662.19
  5805.8 1669.68  5813.0 1670.81  5905.9 1676.31  5976.3 1678.58  5997.9 1680.78
#Mann=3,-1,0
  4634.3    0.05       0  4988.2    0.05       0  5027.7    0.05       0
Bank Sta=4988.2,5027.7
Exp/Cntr=0.3,0.1

Type RM Length L Ch R = 1,19793,422,422,422
BEGIN DESCRIPTION:
Long Creek 35.0
END DESCRIPTION:
XS GIS Cut Line= 3
      1635979.99      6924963.00      1636254.50      6924913.04
      1636904.15      6924743.61
#Sta/Elev= 30
  4714.5 1668.07  4767.8 1668.57  4821.2 1665.59  4851.7 1661.73  4872.1 1657.63
  4879.6 1654.76  4884.7 1654.71  4902.5 1650.87  4938.0 1647.34  4943.2 1645.30
  4983.9 1633.75  4984.6 1631.77  4985.6 1631.27  5023.2 1631.27  5024.2 1631.77
  5025.0 1633.48  5031.8 1637.35  5036.9 1637.06  5045.7 1641.75  5056.0 1643.53
  5077.4 1644.34  5087.0 1643.60  5107.6 1643.45  5159.4 1645.07  5183.6 1645.06
  5376.4 1646.74  5438.4 1645.85  5479.3 1646.01  5507.2 1645.50  5664.9 1646.08
#Mann=5,-1,0
  4714.5    0.05       0  4984.6    0.03       0  5024.2    0.05       0
  5183.6    0.12       0  5479.3    0.05       0
Bank Sta=4984.6,5024.2
Exp/Cntr=0.3,0.1