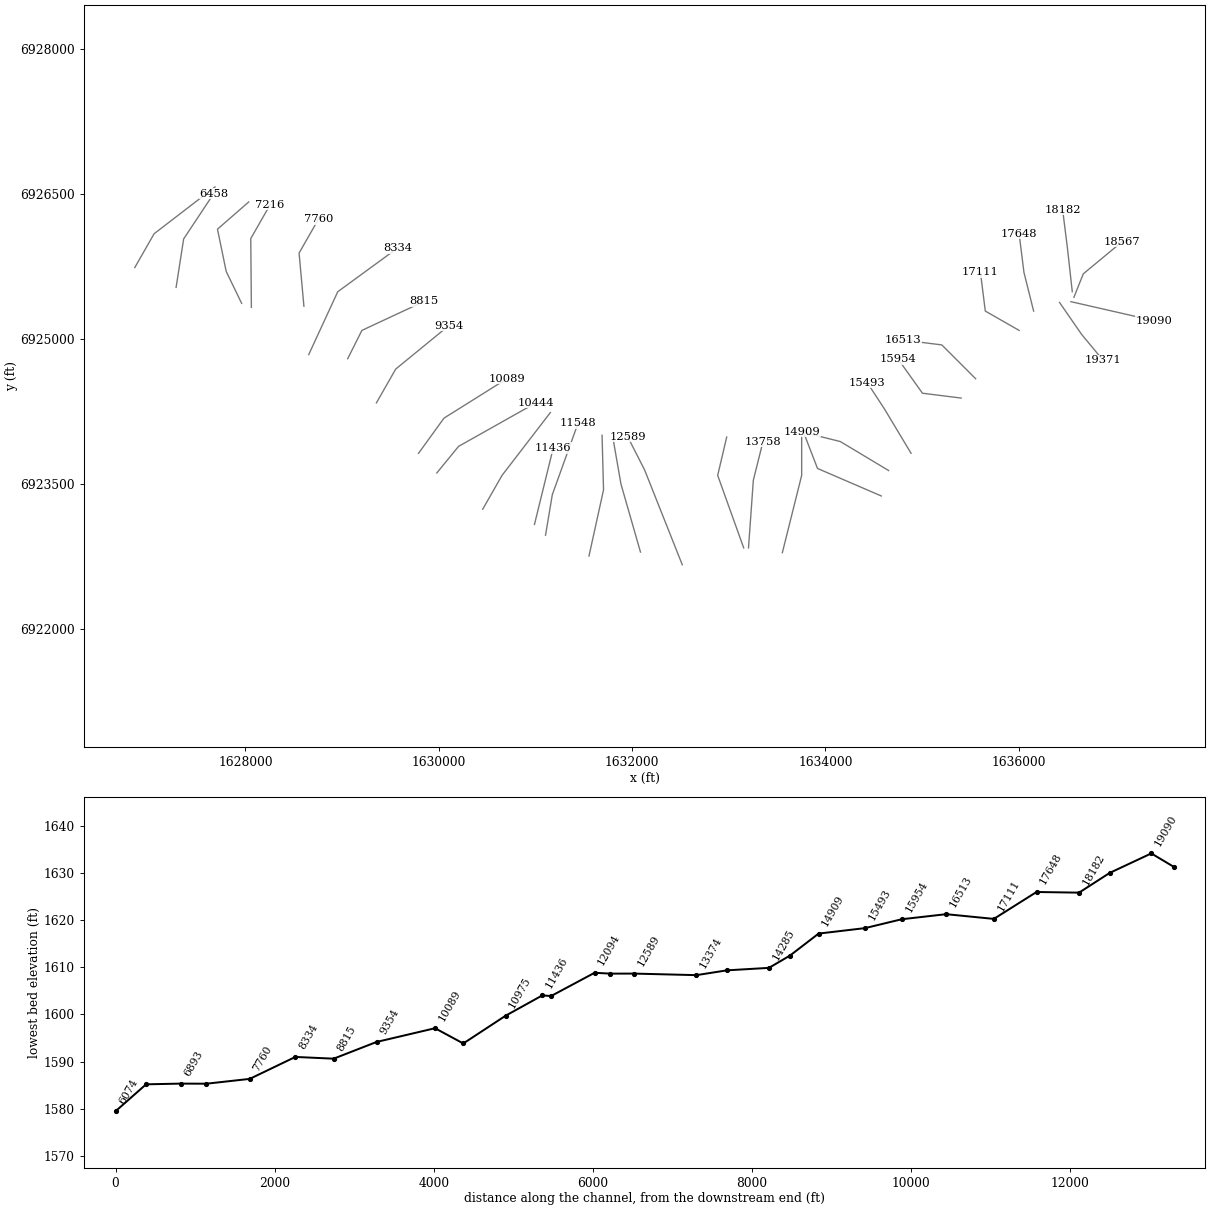
HEC-RAS study Long Creek.prj: Long Creek Base Level Engineering

--- Long Creek.g01 (geometry) --- (continued)

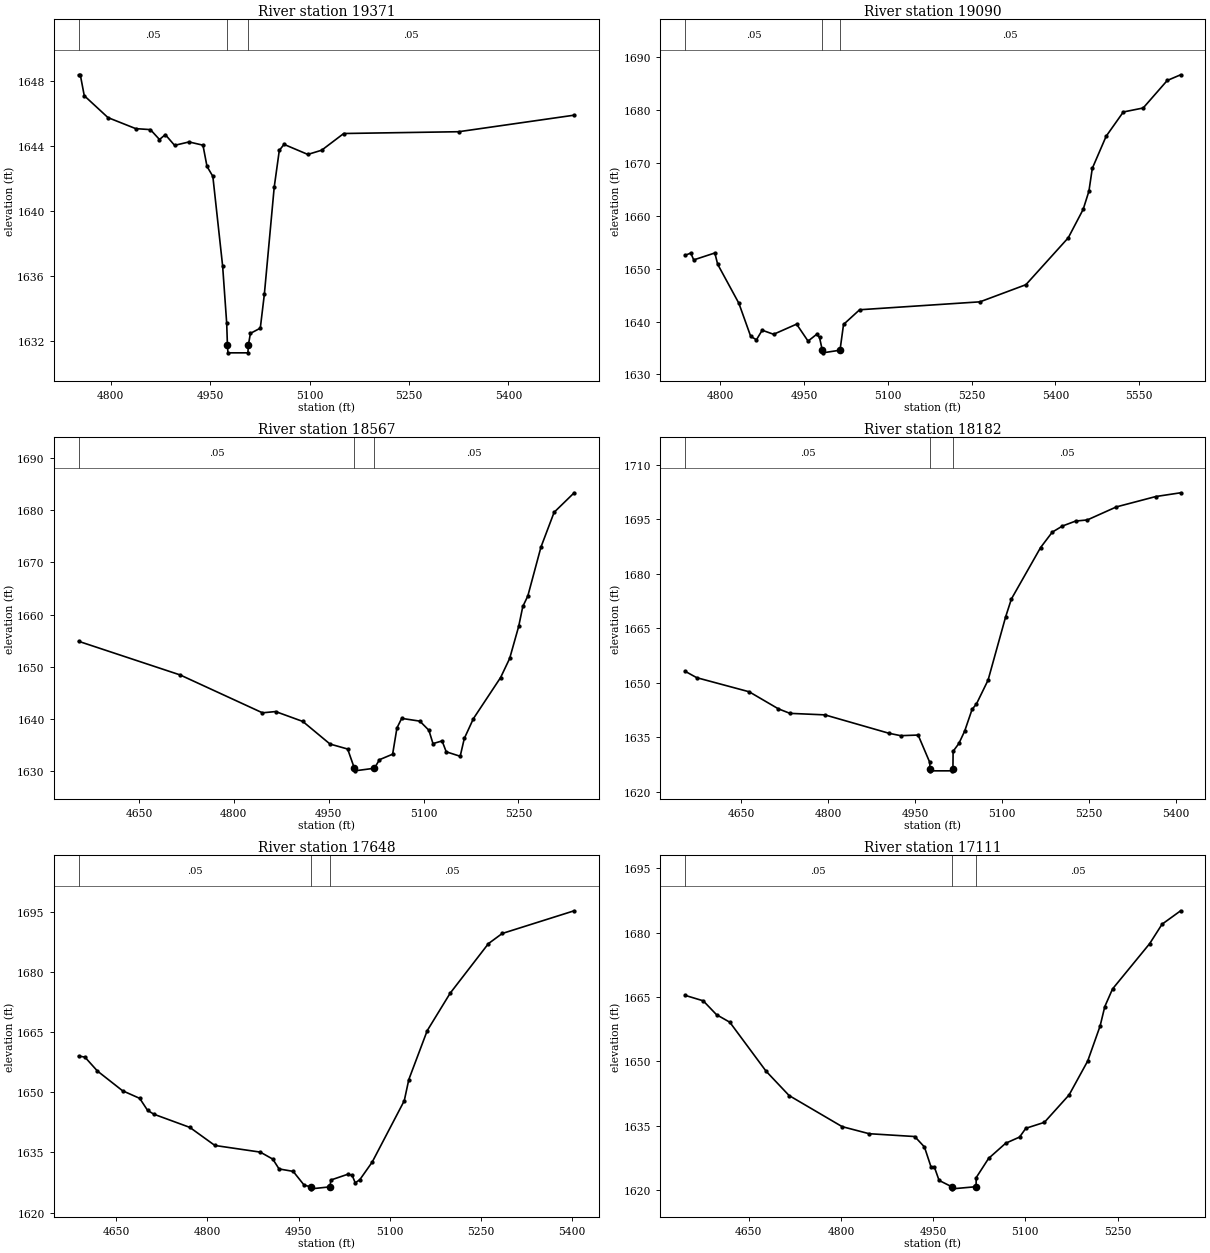
Type RM Length L Ch R = 1,19371,281,281,281
BEGIN DESCRIPTION:
Mapping XS 835f047d
END DESCRIPTION:
XS GIS Cut Line= 3
      1636423.22      6925377.11      1636651.11      6925047.22
      1636872.45      6924780.31
#Sta/Elev= 30
  4751.4 1648.40  4753.9 1648.40  4759.9 1647.11  4795.7 1645.76  4837.6 1645.08
  4859.7 1645.02  4873.4 1644.41  4882.2 1644.71  4896.2 1644.05  4918.0 1644.26
  4939.0 1644.06  4945.1 1642.75  4953.9 1642.14  4968.7 1636.60  4974.8 1633.09
  4975.9 1631.76  4976.7 1631.26  5006.8 1631.26  5007.6 1631.76  5010.6 1632.46
  5025.5 1632.78  5031.6 1634.86  5046.5 1641.47  5054.2 1643.74  5061.3 1644.11
  5097.2 1643.49  5118.1 1643.75  5151.4 1644.78  5324.8 1644.89  5499.1 1645.91
#Mann=3,-1,0
  4751.4    0.05       0  4975.9    0.03       0  5007.6    0.05       0
Bank Sta=4975.9,5007.6
Exp/Cntr=0.3,0.1

Type RM Length L Ch R = 1,19090,523,523,523
BEGIN DESCRIPTION:
Long Creek 34.0
END DESCRIPTION:
XS GIS Cut Line= 2
      1636540.54      6925385.39      1637404.99      6925188.00
#Sta/Elev= 30
  4737.3 1652.53  4747.5 1652.97  4752.7 1651.67  4790.5 1652.98  4795.6 1650.84
  4833.5 1643.47  4854.7 1637.20  4865.0 1636.56  4875.2 1638.37  4895.7 1637.60
  4936.8 1639.52  4957.3 1636.31  4972.7 1637.59  4977.8 1637.02  4982.8 1634.59
  4983.6 1634.09  5014.5 1634.59  5020.8 1639.46  5049.6 1642.24  5265.0 1643.74
  5347.1 1646.98  5422.9 1655.85  5449.6 1661.23  5459.9 1664.68  5465.9 1668.98
  5490.7 1675.06  5521.4 1679.65  5557.0 1680.41  5600.0 1685.61  5624.0 1686.69
#Mann=3,-1,0
  4737.3    0.05       0  4982.8    0.03       0  5014.5    0.05       0
Bank Sta=4982.8,5014.5
Exp/Cntr=0.3,0.1

Type RM Length L Ch R = 1,18567,385,385,385
BEGIN DESCRIPTION:
Mapping XS 7eb5c43b
END DESCRIPTION:
XS GIS Cut Line= 3
      1636571.83      6925430.50      1636669.06      6925673.58
      1637070.90      6926006.13
#Sta/Elev= 30
  4554.7 1654.85  4715.1 1648.39  4845.3 1641.11  4866.1 1641.35  4909.1 1639.45
  4952.1 1635.11  4980.0 1634.15  4990.6 1630.46  4991.4 1629.96  5022.3 1630.46
  5030.3 1632.10  5051.1 1633.16  5057.9 1638.19  5065.4 1640.04  5094.1 1639.51
  5108.4 1637.76  5114.9 1635.19  5129.3 1635.71  5135.8 1633.62  5157.9 1632.76
  5164.4 1636.18  5178.8 1639.99  5221.8 1647.89  5236.1 1651.55  5250.4 1657.73
  5256.9 1661.54  5264.8 1663.55  5285.6 1672.96  5306.4 1679.64  5338.1 1683.39
#Mann=3,-1,0
  4554.7    0.05       0  4990.6    0.05       0  5022.3    0.05       0
Bank Sta=4990.6,5022.3
Exp/Cntr=0.3,0.1

Type RM Length L Ch R = 1,18182,534,534,534
BEGIN DESCRIPTION:
Long Creek 33.0
END DESCRIPTION:
XS GIS Cut Line= 3
      1636555.00      6925487.98      1636505.00      6925938.00
      1636455.00      6926338.00
#Sta/Elev= 30
  4552.6 1653.16  4572.7 1651.40  4663.3 1647.52  4713.6 1642.84  4733.7 1641.59
  4794.1 1641.17  4904.8 1636.11  4924.9 1635.45  4955.1 1635.62  4975.2 1628.10
  4975.4 1626.28  4976.4 1625.78  5014.2 1625.78  5015.2 1626.28  5015.5 1631.15
  5025.5 1633.31  5035.6 1636.76  5048.2 1642.66  5055.8 1644.17  5075.9 1650.73
  5106.2 1668.11  5116.2 1673.05  5166.6 1687.19  5186.8 1691.43  5204.4 1693.11
  5227.1 1694.47  5247.3 1694.78  5297.6 1698.37  5365.7 1701.22  5408.5 1702.25
#Mann=3,-1,0
  4552.6    0.05       0  4975.4    0.05       0  5015.2    0.05       0
Bank Sta=4975.4,5015.2
Exp/Cntr=0.3,0.1

Type RM Length L Ch R = 1,17648,537,537,537
BEGIN DESCRIPTION:
Long Creek 32.0
END DESCRIPTION:
XS GIS Cut Line= 3
      1636155.00      6925288.00      1636055.00      6925688.00
      1636005.00      6926087.98
#Sta/Elev= 30
  4588.0 1659.07  4598.3 1658.82  4618.9 1655.34  4660.2 1650.42  4688.5 1648.51
  4701.4 1645.53  4711.7 1644.56  4771.0 1641.26  4812.2 1636.75  4886.9 1635.09
  4907.5 1633.34  4917.8 1630.89  4941.0 1630.28  4959.1 1626.84  4969.9 1626.42
  4970.7 1625.92  5001.8 1626.42  5002.8 1628.11  5030.5 1629.54  5038.1 1629.31
  5043.1 1627.41  5050.7 1628.21  5070.9 1632.56  5123.8 1647.91  5131.3 1653.21
  5161.6 1665.42  5199.3 1674.76  5262.3 1687.15  5285.0 1689.68  5403.4 1695.35
#Mann=3,-1,0
  4588.0    0.05       0  4969.9    0.05       0  5001.8    0.05       0
Bank Sta=4969.9,5001.8
Exp/Cntr=0.3,0.1

Type RM Length L Ch R = 1,17111,598,598,598
BEGIN DESCRIPTION:
Long Creek 31.0
END DESCRIPTION:
XS GIS Cut Line= 3
      1636004.99      6925088.01      1635655.00      6925288.00
      1635605.00      6925687.98
#Sta/Elev= 30
  4546.5 1665.39  4576.0 1664.11  4597.6 1660.88  4619.2 1659.12  4678.2 1647.69
  4715.7 1642.00  4802.0 1634.74  4845.9 1633.09  4920.1 1632.43  4935.9 1629.99
  4946.7 1625.29  4952.1 1625.29  4959.7 1622.19  4980.1 1620.72  4981.1 1620.22
  5019.9 1620.72  5020.1 1622.84  5040.3 1627.33  5068.0 1630.86  5090.7 1632.31
  5100.8 1634.35  5131.0 1635.74  5171.3 1642.16  5201.5 1650.06  5221.7 1658.24
  5229.3 1662.76  5241.9 1666.88  5302.3 1677.46  5322.5 1682.00  5352.7 1685.13
#Mann=3,-1,0
  4546.5    0.05       0  4980.1    0.03       0  5019.9    0.05       0
Bank Sta=4980.1,5019.9
Exp/Cntr=0.3,0.1

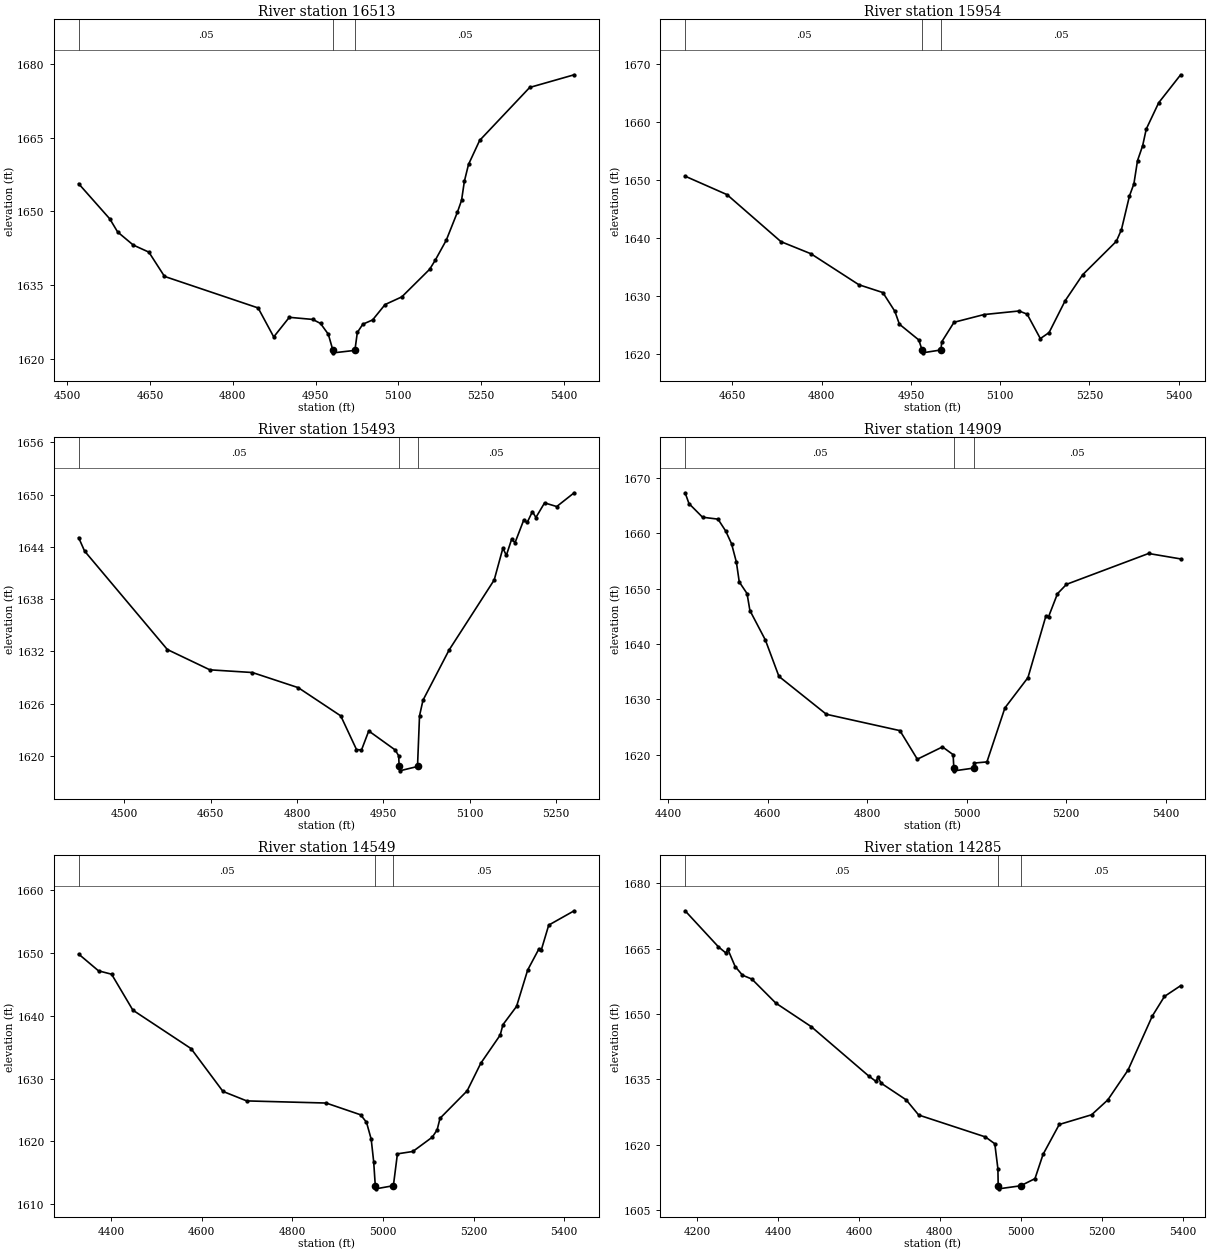
Type RM Length L Ch R = 1,16513,559,559,559
BEGIN DESCRIPTION:
Long Creek 30.0
END DESCRIPTION:
XS GIS Cut Line= 3
      1635555.00      6924588.00      1635205.00      6924938.00
      1634804.99      6924988.00
#Sta/Elev= 30
  4520.6 1655.65  4577.2 1648.47  4591.3 1645.82  4619.6 1643.16  4647.9 1641.72
  4676.2 1636.78  4845.9 1630.36  4874.2 1624.46  4902.4 1628.45  4944.9 1628.02
  4959.0 1627.20  4973.1 1625.01  4981.5 1621.72  4982.5 1621.22  5021.3 1621.72
  5025.7 1625.37  5035.7 1627.05  5053.4 1627.92  5076.0 1631.05  5106.3 1632.61
  5156.7 1638.22  5166.7 1640.03  5186.9 1644.15  5207.1 1649.86  5214.6 1652.26
  5219.7 1656.14  5227.2 1659.57  5247.4 1664.46  5338.1 1675.24  5418.7 1677.82
#Mann=3,-1,0
  4520.6    0.05       0  4981.5    0.05       0  5021.3    0.05       0
Bank Sta=4981.5,5021.3
Exp/Cntr=0.3,0.1

Type RM Length L Ch R = 1,15954,461,461,461
BEGIN DESCRIPTION:
Long Creek 29.0
END DESCRIPTION:
XS GIS Cut Line= 3
      1635404.98      6924388.00      1635005.00      6924438.00
      1634755.00      6924787.99
#Sta/Elev= 30
  4570.3 1650.66  4640.8 1647.47  4731.5 1639.35  4781.9 1637.26  4862.5 1631.91
  4902.8 1630.56  4923.0 1627.32  4930.6 1625.10  4963.3 1622.37  4968.7 1620.65
  4969.5 1620.15  5000.6 1620.65  5001.7 1622.03  5022.5 1625.43  5072.9 1626.76
  5131.9 1627.38  5145.4 1626.83  5167.6 1622.61  5182.3 1623.65  5209.3 1629.14
  5238.8 1633.64  5295.4 1639.41  5304.0 1641.44  5317.5 1647.26  5324.9 1649.33
  5331.0 1653.35  5339.6 1655.91  5345.7 1658.80  5366.6 1663.34  5403.5 1668.17
#Mann=3,-1,0
  4570.3    0.05       0  4968.7    0.03       0  5000.6    0.05       0
Bank Sta=4968.7,5000.6
Exp/Cntr=0.3,0.1

Type RM Length L Ch R = 1,15493,584,584,584
BEGIN DESCRIPTION:
Long Creek 28.0
END DESCRIPTION:
XS GIS Cut Line= 3
      1634886.79      6923816.74      1634613.35      6924272.48
      1634433.24      6924548.06
#Sta/Elev= 30
  4420.9 1645.05  4431.2 1643.51  4575.0 1632.20  4648.8 1629.87  4722.7 1629.56
  4802.4 1627.82  4876.2 1624.58  4903.5 1620.72  4912.2 1620.66  4924.8 1622.85
  4970.9 1620.66  4976.8 1619.99  4977.6 1618.77  4978.4 1618.27  5009.5 1618.77
  5013.0 1624.59  5019.0 1626.38  5064.3 1632.14  5142.7 1640.19  5157.8 1643.84
  5163.8 1643.01  5172.9 1644.85  5178.9 1644.47  5194.0 1647.07  5200.0 1646.79
  5209.1 1648.04  5215.1 1647.36  5230.2 1649.04  5251.3 1648.62  5281.6 1650.20
#Mann=3,-1,0
  4420.9    0.05       0  4977.6    0.03       0  5009.5    0.05       0
Bank Sta=4977.6,5009.5
Exp/Cntr=0.3,0.1

Type RM Length L Ch R = 1,14909,360,360,360
BEGIN DESCRIPTION:
Long Creek 27.0
END DESCRIPTION:
XS GIS Cut Line= 3
      1634655.00      6923638.00      1634155.00      6923938.00
      1633755.01      6924038.00
#Sta/Elev= 30
  4434.3 1667.31  4442.1 1665.36  4469.3 1662.90  4500.4 1662.55  4515.9 1660.40
  4527.6 1658.11  4537.3 1654.80  4543.1 1651.21  4558.7 1649.12  4564.5 1646.05
  4595.6 1640.72  4622.8 1634.16  4718.1 1627.32  4865.8 1624.37  4900.8 1619.21
  4951.3 1621.43  4972.7 1620.03  4974.1 1617.61  4975.1 1617.11  5014.1 1617.61
  5014.5 1618.51  5040.6 1618.72  5076.7 1628.47  5123.0 1633.94  5159.1 1645.08
  5164.3 1644.91  5182.3 1649.09  5200.4 1650.78  5365.3 1656.35  5429.7 1655.37
#Mann=3,-1,0
  4434.3    0.05       0  4974.1    0.03       0  5014.1    0.05       0
Bank Sta=4974.1,5014.1
Exp/Cntr=0.3,0.1

Type RM Length L Ch R = 1,14549,264,264,264
BEGIN DESCRIPTION:
Mapping XS 794667cd
END DESCRIPTION:
XS GIS Cut Line= 3
      1634578.77      6923374.97      1633919.06      6923659.69
      1633783.63      6924010.42
#Sta/Elev= 30
  4327.8 1649.83  4371.7 1647.16  4400.6 1646.62  4447.6 1640.90  4576.1 1634.78
  4646.6 1627.96  4699.1 1626.45  4874.5 1626.11  4950.5 1624.24  4963.6 1623.05
  4974.0 1620.35  4979.5 1616.75  4983.0 1612.95  4984.0 1612.45  5023.0 1612.95
  5031.9 1618.02  5066.0 1618.40  5108.8 1620.67  5119.6 1621.83  5126.0 1623.68
  5185.9 1628.05  5216.0 1632.44  5258.9 1636.93  5265.0 1638.59  5295.0 1641.49
  5319.6 1647.29  5344.2 1650.62  5349.6 1650.46  5366.1 1654.44  5422.3 1656.72
#Mann=3,-1,0
  4327.8    0.05       0  4983.0    0.05       0  5023.0    0.05       0
Bank Sta=4983,5023
Exp/Cntr=0.3,0.1

Type RM Length L Ch R = 1,14285,527,527,527
BEGIN DESCRIPTION:
Long Creek 26.0
END DESCRIPTION:
XS GIS Cut Line= 3
      1633554.99      6922787.97      1633755.00      6923588.00
      1633755.00      6923988.04
#Sta/Elev= 30
  4170.4 1673.70  4252.9 1665.41  4270.9 1664.03  4276.1 1664.82  4294.1 1660.90
  4312.2 1658.91  4335.4 1658.02  4394.6 1652.50  4482.2 1647.09  4624.0 1635.78
  4642.0 1634.53  4647.2 1635.53  4654.9 1634.11  4716.7 1630.29  4747.7 1626.80
  4912.6 1621.77  4935.8 1620.20  4943.5 1614.45  4944.2 1610.55  4945.4 1609.85
  4999.6 1610.55  5035.1 1612.19  5055.1 1617.77  5095.1 1624.63  5175.1 1626.86
  5215.1 1630.27  5265.1 1637.12  5325.1 1649.53  5355.1 1654.03  5395.1 1656.50
#Mann=3,-1,0
  4170.4    0.05       0  4944.2    0.03       0  4999.6    0.05       0
Bank Sta=4944.2,4999.6
Exp/Cntr=0.3,0.1

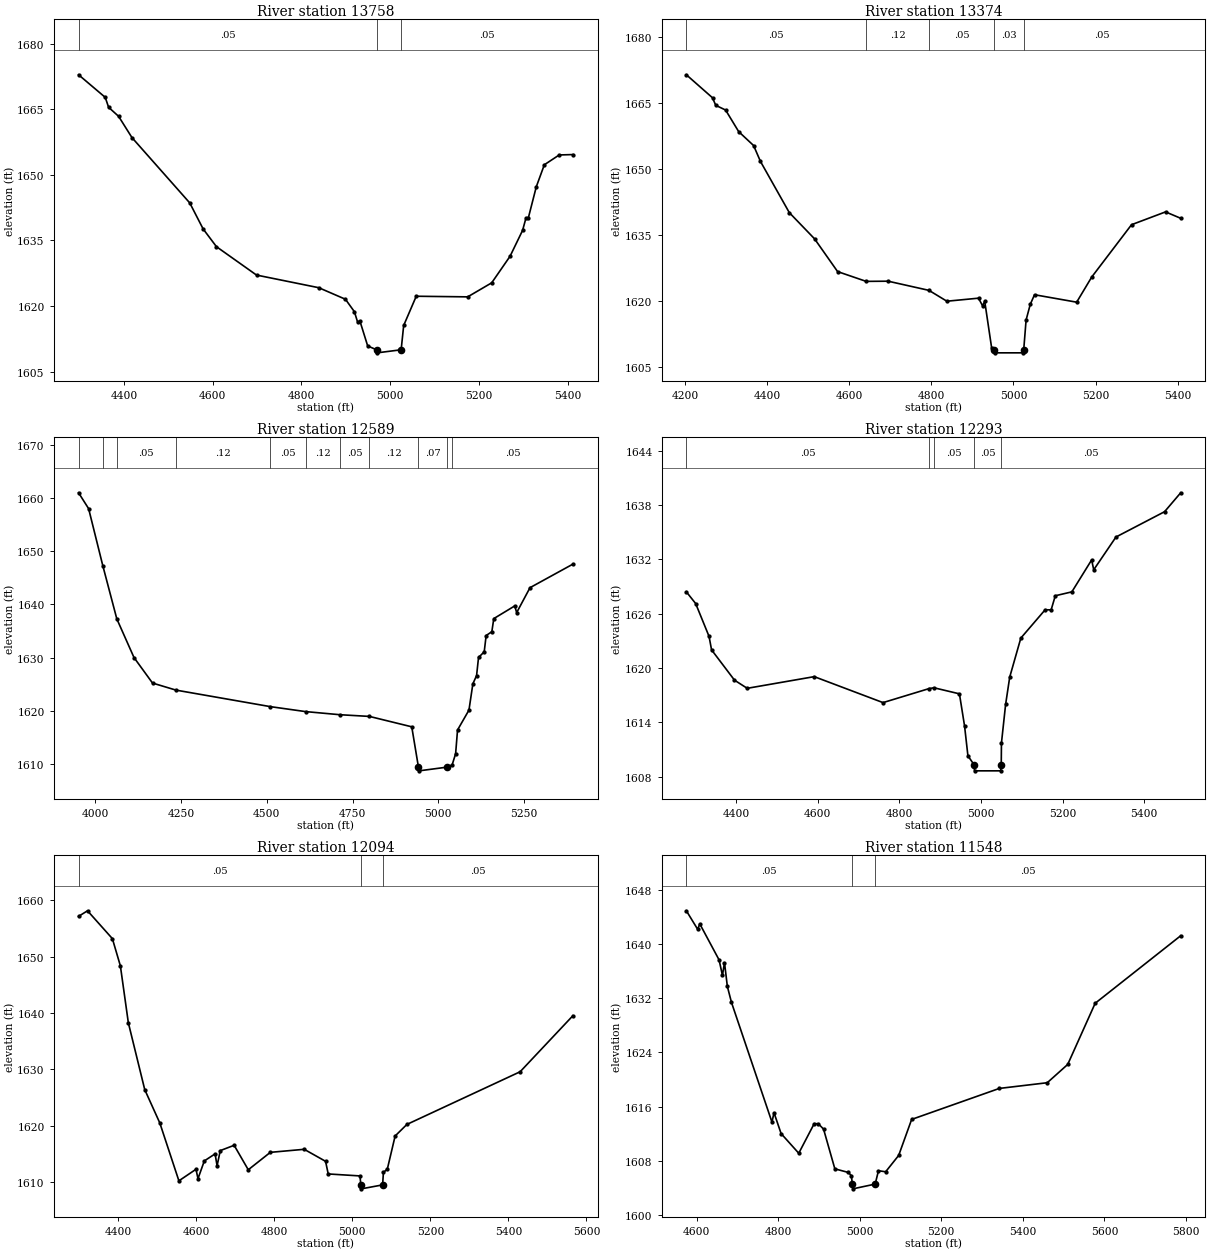
Type RM Length L Ch R = 1,13758,384,384,384
BEGIN DESCRIPTION:
Long Creek 25.0
END DESCRIPTION:
XS GIS Cut Line= 3
      1633205.00      6922838.01      1633255.00      6923538.00
      1633355.00      6923938.02
#Sta/Elev= 30
  4297.6 1672.86  4357.7 1667.70  4365.3 1665.43  4387.8 1663.37  4417.9 1658.51
  4548.2 1643.58  4578.3 1637.64  4608.4 1633.58  4698.6 1627.10  4839.0 1624.21
  4899.1 1621.57  4919.2 1618.73  4926.7 1616.28  4931.7 1616.59  4949.2 1610.90
  4969.2 1610.03  4970.4 1609.33  5024.6 1610.03  5030.3 1615.58  5058.6 1622.26
  5174.6 1622.12  5228.7 1625.33  5270.0 1631.39  5298.3 1637.31  5306.0 1640.17
  5311.2 1640.14  5329.2 1647.28  5347.3 1652.30  5380.8 1654.54  5411.7 1654.63
#Mann=3,-1,0
  4297.6    0.05       0  4969.2    0.03       0  5024.6    0.05       0
Bank Sta=4969.2,5024.6
Exp/Cntr=0.3,0.1

Type RM Length L Ch R = 1,13374,785,785,785
BEGIN DESCRIPTION:
Long Creek 24.0
END DESCRIPTION:
XS GIS Cut Line= 3
      1633155.00      6922838.00      1632886.14      6923587.97
      1632979.48      6923984.63
#Sta/Elev= 30
  4203.3 1671.38  4267.0 1666.16  4274.9 1664.45  4298.9 1663.38  4330.8 1658.48
  4367.1 1655.33  4383.9 1651.71  4454.1 1640.11  4515.6 1634.17  4571.7 1626.74
  4641.3 1624.52  4694.8 1624.56  4794.3 1622.48  4837.9 1620.02  4915.0 1620.71
  4924.8 1618.99  4930.1 1620.01  4946.9 1609.47  4953.1 1609.01  4954.6 1608.31
  5023.5 1608.31  5025.1 1609.01  5030.9 1615.76  5041.1 1619.32  5051.4 1621.49
  5154.1 1619.80  5190.8 1625.51  5287.7 1637.37  5370.6 1640.28  5407.5 1638.83
#Mann=5,-1,0
  4203.3    0.05       0  4641.3    0.12       0  4794.3    0.05       0
  4953.1    0.03       0  5025.1    0.05       0
Bank Sta=4953.1,5025.1
Exp/Cntr=0.3,0.1

Type RM Length L Ch R = 1,12589,296,296,296
BEGIN DESCRIPTION:
Long Creek 23.0
END DESCRIPTION:
XS GIS Cut Line= 3
      1632519.76      6922663.13      1632130.86      6923642.33
      1631955.02      6923987.97
#Sta/Elev= 30
  3951.1 1661.06  3980.4 1658.07  4021.7 1647.33  4062.6 1637.29  4112.7 1630.00
  4166.7 1625.19  4235.0 1623.86  4510.6 1620.74  4612.8 1619.81  4713.1 1619.22
  4799.1 1618.90  4922.6 1616.94  4942.1 1609.34  4943.9 1608.64  5025.8 1609.34
  5040.3 1609.75  5050.5 1611.87  5056.1 1616.34  5089.4 1620.09  5100.8 1625.05
  5111.6 1626.59  5117.3 1630.01  5133.9 1631.08  5139.5 1634.15  5156.1 1634.87
  5161.8 1637.34  5222.9 1639.73  5228.5 1638.47  5267.4 1643.17  5392.5 1647.61
#Mann=11,-1,0
  3951.1    0.05       0  4021.7    0.12       0  4062.6    0.05       0
  4235.0    0.12       0  4510.6    0.05       0  4612.8    0.12       0
  4713.1    0.05       0  4799.1    0.12       0  4942.1    0.07       0
  5025.8    0.12       0  5040.3    0.05       0
Bank Sta=4942.1,5025.8
Exp/Cntr=0.3,0.1

Type RM Length L Ch R = 1,12293,199,199,199
BEGIN DESCRIPTION:
Mapping XS b3ba1945
END DESCRIPTION:
XS GIS Cut Line= 3
      1632087.32      6922794.57      1631885.48      6923497.74
      1631803.01      6923970.84
#Sta/Elev= 30
  4277.7 1628.41  4300.5 1627.12  4333.3 1623.49  4339.5 1622.00  4395.7 1618.65
  4426.9 1617.75  4591.2 1619.04  4759.8 1616.17  4872.7 1617.72  4884.7 1617.81
  4947.1 1617.14  4959.7 1613.58  4967.9 1610.29  4982.6 1609.33  4984.2 1608.63
  5048.1 1608.63  5049.6 1609.33  5050.1 1611.70  5060.3 1615.97  5070.4 1619.00
  5097.6 1623.30  5157.2 1626.43  5171.9 1626.42  5182.1 1627.98  5222.7 1628.41
  5271.2 1631.94  5276.3 1630.85  5330.8 1634.47  5450.0 1637.27  5489.5 1639.36
#Mann=5,-1,0
  4277.7    0.05       0  4872.7    0.12       0  4884.7    0.05       0
  4982.6    0.05       0  5049.6    0.05       0
Bank Sta=4982.6,5049.6
Exp/Cntr=0.3,0.1

Type RM Length L Ch R = 1,12094,546,546,546
BEGIN DESCRIPTION:
Long Creek 22.0
END DESCRIPTION:
XS GIS Cut Line= 3
      1631554.48      6922753.45      1631705.00      6923438.00
      1631689.90      6924003.19
#Sta/Elev= 30
  4298.9 1657.12  4321.8 1658.11  4385.5 1653.17  4406.0 1648.34  4426.4 1638.25
  4468.4 1626.40  4507.0 1620.49  4555.9 1610.23  4599.7 1612.28  4604.8 1610.61
  4621.0 1613.76  4648.6 1615.01  4653.7 1612.90  4661.9 1615.59  4697.4 1616.53
  4733.6 1612.19  4790.1 1615.28  4876.9 1615.82  4931.6 1613.69  4938.4 1611.45
  5019.8 1611.10  5021.9 1609.51  5023.2 1608.81  5077.7 1609.51  5079.8 1611.72
  5089.8 1612.31  5109.8 1618.18  5139.9 1620.23  5430.0 1629.57  5565.2 1639.51
#Mann=3,-1,0
  4298.9    0.05       0  5021.9    0.05       0  5077.7    0.05       0
Bank Sta=5021.9,5077.7
Exp/Cntr=0.3,0.1

Type RM Length L Ch R = 1,11548,112,112,112
BEGIN DESCRIPTION:
Long Creek 21.0
END DESCRIPTION:
XS GIS Cut Line= 3
      1631104.87      6922968.90      1631175.03      6923388.07
      1631441.67      6924128.63
#Sta/Elev= 30
  4575.0 1644.90  4602.8 1642.16  4607.8 1642.98  4655.2 1637.66  4663.5 1635.37
  4668.5 1637.25  4675.5 1633.75  4685.6 1631.39  4784.9 1613.73  4789.9 1615.12
  4807.3 1612.04  4850.6 1609.14  4888.4 1613.50  4898.5 1613.49  4911.4 1612.70
  4939.1 1606.84  4972.1 1606.31  4979.6 1605.83  4982.0 1604.59  4983.2 1603.89
  5038.0 1604.59  5046.0 1606.56  5063.7 1606.41  5095.6 1608.82  5127.4 1614.13
  5342.4 1618.70  5459.9 1619.54  5510.1 1622.24  5577.4 1631.26  5787.1 1641.22
#Mann=3,-1,0
  4575.0    0.05       0  4982.0    0.05       0  5038.0    0.05       0
Bank Sta=4982,5038
Exp/Cntr=0.3,0.1

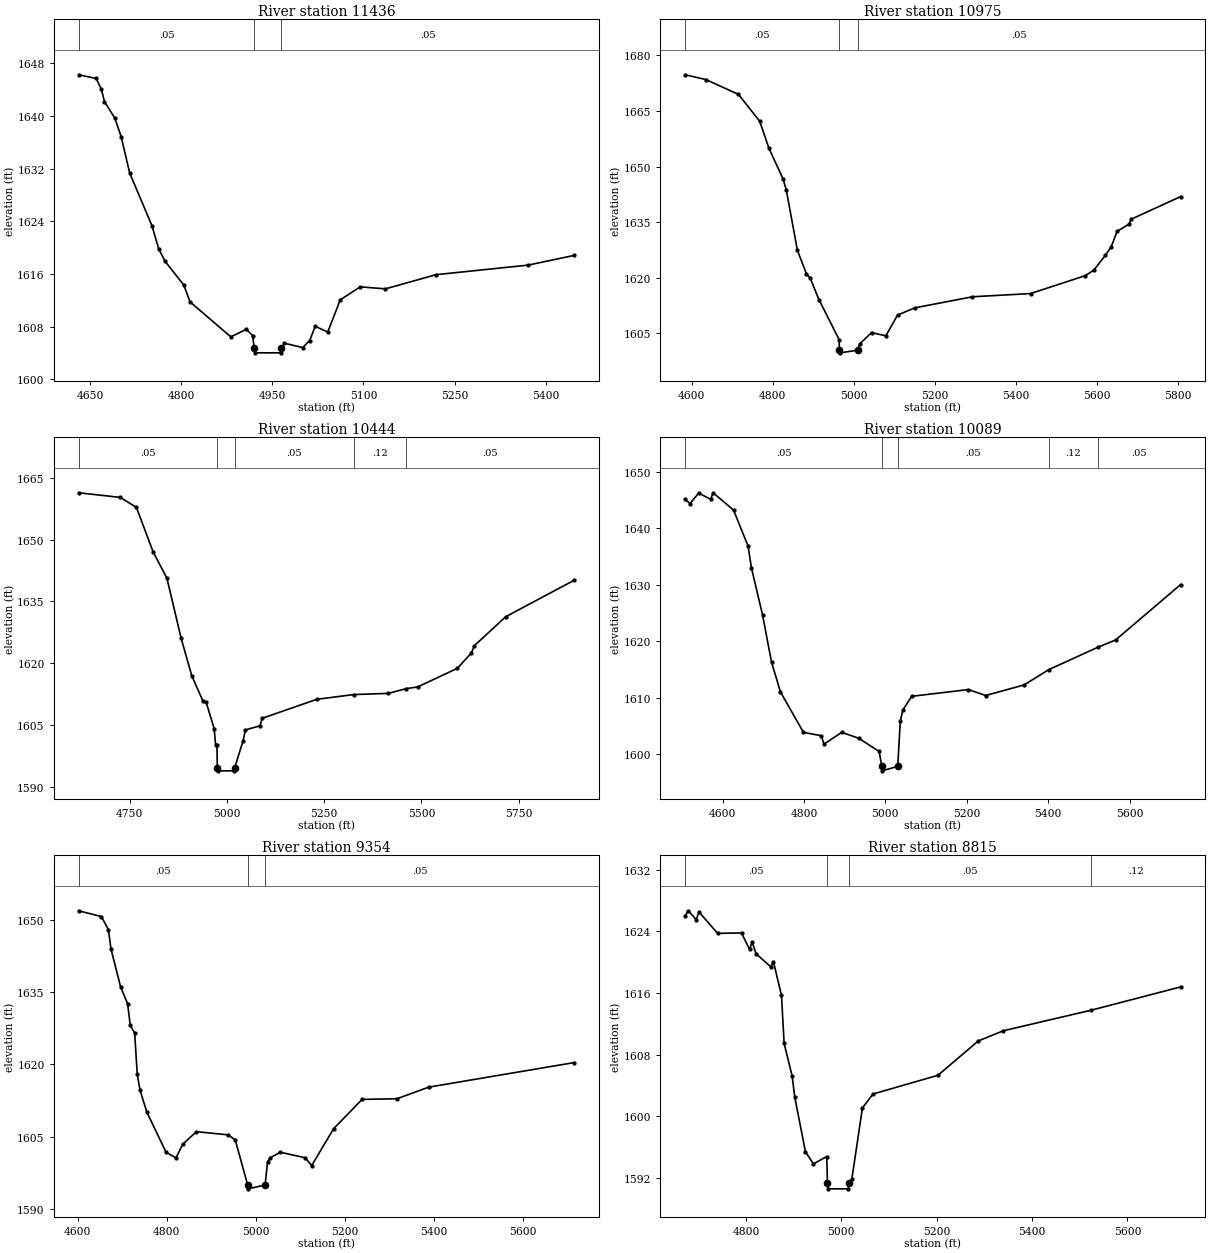
Type RM Length L Ch R = 1,11436,461,461,461
BEGIN DESCRIPTION:
Mapping XS 89790579
END DESCRIPTION:
XS GIS Cut Line= 2
      1630990.29      6923080.03      1631184.73      6923871.70
#Sta/Elev= 30
  4631.4 1646.24  4660.2 1645.68  4668.7 1644.06  4673.9 1642.17  4691.1 1639.63
  4701.4 1636.82  4715.4 1631.32  4751.9 1623.34  4763.2 1619.79  4773.5 1617.93
  4804.4 1614.30  4814.7 1611.75  4881.7 1606.44  4907.3 1607.59  4917.6 1606.62
  4920.3 1604.71  4921.3 1604.01  4964.1 1604.01  4965.1 1604.71  4969.9 1605.47
  5000.0 1604.81  5011.5 1605.88  5020.6 1608.04  5041.2 1607.17  5061.8 1612.06
  5094.6 1614.03  5136.2 1613.73  5219.3 1615.88  5370.7 1617.33  5446.6 1618.81
#Mann=3,-1,0
  4631.4    0.05       0  4920.3    0.05       0  4965.1    0.05       0
Bank Sta=4920.3,4965.1
Exp/Cntr=0.3,0.1

Type RM Length L Ch R = 1,10975,531,531,531
BEGIN DESCRIPTION:
Long Creek 20.0
END DESCRIPTION:
XS GIS Cut Line= 3
      1630454.99      6923237.99      1630655.00      6923588.00
      1631155.01      6924238.01
#Sta/Elev= 30
  4583.9 1674.79  4635.0 1673.51  4715.6 1669.50  4768.2 1662.22  4790.5 1655.06
  4825.8 1646.63  4833.7 1643.67  4861.1 1627.41  4883.4 1621.03  4892.7 1619.91
  4914.3 1614.08  4964.0 1603.30  4964.9 1600.41  4965.9 1599.71  5009.7 1600.41
  5015.1 1602.12  5044.1 1605.17  5079.4 1604.31  5108.5 1609.92  5151.0 1611.86
  5293.3 1614.85  5436.5 1615.71  5571.5 1620.54  5592.6 1622.02  5621.3 1626.04
  5635.8 1628.36  5650.3 1632.53  5679.3 1634.42  5685.7 1635.82  5807.1 1641.90
#Mann=3,-1,0
  4583.9    0.05       0  4964.9    0.05       0  5009.7    0.05       0
Bank Sta=4964.9,5009.7
Exp/Cntr=0.3,0.1

Type RM Length L Ch R = 1,10444,355,355,355
BEGIN DESCRIPTION:
Long Creek 19.0
END DESCRIPTION:
XS GIS Cut Line= 3
      1629980.03      6923613.04      1630205.00      6923888.00
      1631004.96      6924337.98
#Sta/Elev= 30
  4619.2 1661.41  4726.1 1660.29  4767.7 1657.86  4810.8 1646.99  4846.0 1640.67
  4882.6 1626.03  4909.9 1616.93  4938.6 1610.79  4946.5 1610.62  4967.3 1604.12
  4971.2 1600.23  4974.5 1600.23  4975.5 1594.64  4976.6 1593.84  5019.4 1593.84
  5020.3 1594.64  5041.7 1601.14  5047.5 1603.78  5085.1 1604.78  5090.8 1606.61
  5231.0 1611.22  5326.3 1612.38  5414.6 1612.66  5461.2 1613.83  5489.8 1614.21
  5592.4 1618.76  5628.5 1622.52  5635.8 1624.25  5716.7 1631.31  5892.3 1640.15
#Mann=5,-1,0
  4619.2    0.05       0  4975.5    0.05       0  5020.3    0.05       0
  5326.3    0.12       0  5461.2    0.05       0
Bank Sta=4975.5,5020.3
Exp/Cntr=0.3,0.1

Type RM Length L Ch R = 1,10089,735,735,735
BEGIN DESCRIPTION:
Long Creek 18.0
END DESCRIPTION:
XS GIS Cut Line= 3
      1629790.57      6923815.92      1630054.47      6924180.52
      1630705.00      6924588.00
#Sta/Elev= 30
  4507.9 1645.06  4520.3 1644.34  4541.2 1646.19  4570.6 1645.09  4576.8 1646.24
  4627.0 1643.18  4662.6 1636.81  4671.0 1632.92  4698.2 1624.66  4720.3 1616.28
  4742.3 1611.01  4798.7 1603.88  4842.8 1603.27  4849.0 1601.79  4893.1 1603.88
  4934.8 1602.82  4984.8 1600.49  4991.2 1597.87  4992.1 1597.07  5030.4 1597.87
  5036.7 1605.81  5042.6 1607.79  5064.8 1610.25  5204.0 1611.44  5246.5 1610.39
  5340.8 1612.26  5402.0 1614.98  5521.7 1618.91  5565.9 1620.22  5725.6 1630.01
#Mann=5,-1,0
  4507.9    0.05       0  4991.2    0.05       0  5030.4    0.05       0
  5402.0    0.12       0  5521.7    0.05       0
Bank Sta=4991.2,5030.4
Exp/Cntr=0.3,0.1

Type RM Length L Ch R = 1,9354,539,539,539
BEGIN DESCRIPTION:
Long Creek 17.0
END DESCRIPTION:
XS GIS Cut Line= 3
      1629355.00      6924338.00      1629555.00      6924688.00
      1630104.96      6925137.97
#Sta/Elev= 30
  4602.3 1651.86  4653.4 1650.66  4669.2 1647.96  4675.0 1643.93  4696.6 1636.08
  4712.4 1632.56  4718.2 1628.15  4728.3 1626.43  4734.0 1617.92  4740.5 1614.57
  4755.6 1610.08  4798.8 1601.75  4821.1 1600.57  4836.3 1603.43  4867.2 1606.02
  4938.5 1605.36  4954.3 1604.30  4982.2 1594.96  4983.0 1594.16  5021.4 1594.96
  5026.9 1599.78  5033.4 1600.64  5055.7 1601.76  5111.6 1600.60  5126.0 1598.99
  5175.5 1606.65  5239.4 1612.72  5317.7 1612.86  5389.4 1615.27  5716.0 1620.36
#Mann=3,-1,0
  4602.3    0.05       0  4982.2    0.05       0  5021.4    0.05       0
Bank Sta=4982.2,5021.4
Exp/Cntr=0.3,0.1

Type RM Length L Ch R = 1,8815,481,481,481
BEGIN DESCRIPTION:
Long Creek 16.0
END DESCRIPTION:
XS GIS Cut Line= 3
      1629057.97      6924795.14      1629205.00      6925088.00
      1629849.65      6925388.87
#Sta/Elev= 30
  4672.4 1626.00  4679.1 1626.66  4695.8 1625.51  4701.4 1626.51  4740.5 1623.74
  4790.7 1623.78  4807.5 1621.67  4813.1 1622.60  4821.1 1621.09  4852.1 1619.40
  4857.7 1620.06  4874.5 1615.69  4880.1 1609.46  4896.8 1605.25  4902.4 1602.50
  4924.7 1595.43  4941.5 1593.86  4969.4 1594.80  4970.9 1591.42  4971.9 1590.62
  5014.9 1590.62  5015.8 1591.42  5022.2 1591.93  5044.2 1601.10  5066.3 1602.91
  5202.7 1605.34  5287.0 1609.78  5339.8 1611.11  5523.6 1613.77  5711.5 1616.79
#Mann=4,-1,0
  4672.4    0.05       0  4970.9    0.05       0  5015.8    0.05       0
  5523.6    0.12       0
Bank Sta=4970.9,5015.8
Exp/Cntr=0.3,0.1

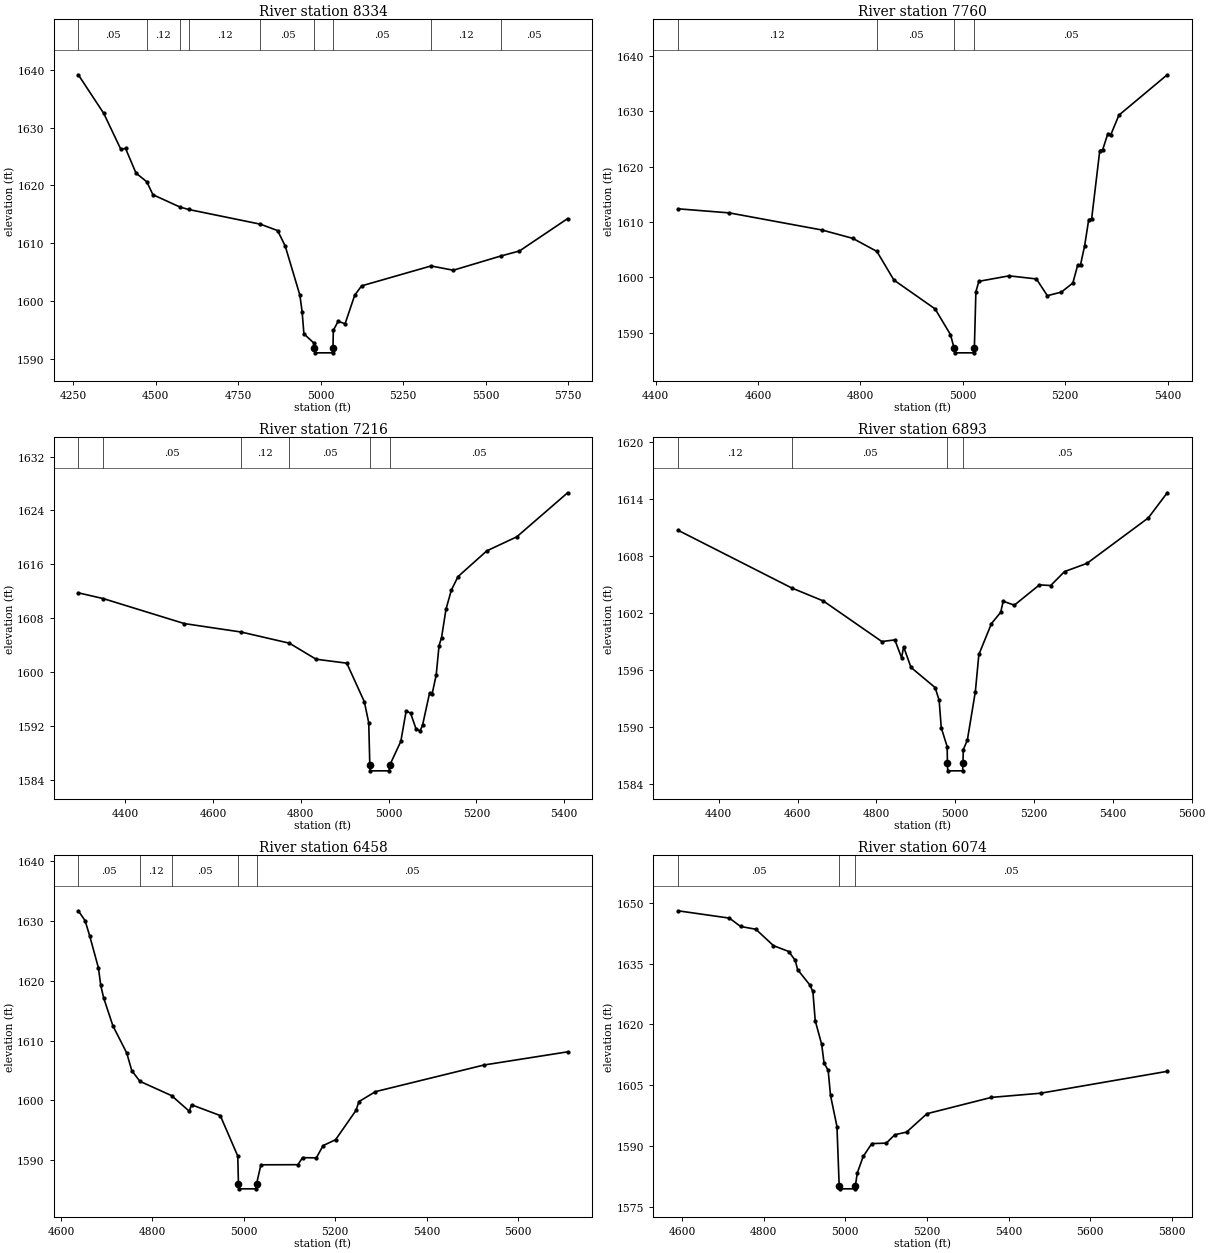
Type RM Length L Ch R = 1,8334,574,574,574
BEGIN DESCRIPTION:
Long Creek 15.0
END DESCRIPTION:
XS GIS Cut Line= 3
      1628654.99      6924837.98      1628955.00      6925488.00
      1629575.32      6925940.95
#Sta/Elev= 30
  4264.9 1639.19  4342.0 1632.50  4393.9 1626.26  4408.1 1626.43  4439.8 1622.15
  4472.6 1620.64  4491.2 1618.40  4573.3 1616.26  4599.6 1615.84  4817.3 1613.29
  4869.3 1612.18  4892.2 1609.53  4936.8 1601.00  4943.6 1598.15  4949.1 1594.28
  4980.8 1592.61  4980.9 1591.79  4982.2 1590.99  5035.9 1590.99  5037.2 1591.79
  5038.3 1594.88  5053.0 1596.47  5073.9 1596.02  5103.2 1600.98  5124.1 1602.60
  5334.6 1606.05  5402.1 1605.31  5545.4 1607.76  5602.9 1608.65  5748.9 1614.26
#Mann=9,-1,0
  4264.9    0.05       0  4472.6    0.12       0  4573.3    0.05       0
  4599.6    0.12       0  4817.3    0.05       0  4980.9    0.03       0
  5037.2    0.05       0  5334.6    0.12       0  5545.4    0.05       0
Bank Sta=4980.9,5037.2
Exp/Cntr=0.3,0.1

Type RM Length L Ch R = 1,7760,544,544,544
BEGIN DESCRIPTION:
Long Creek 14.0
END DESCRIPTION:
XS GIS Cut Line= 3
      1628605.00      6925337.99      1628555.00      6925888.00
      1628755.00      6926238.00
#Sta/Elev= 30
  4443.6 1612.36  4544.0 1611.62  4724.8 1608.53  4785.0 1607.02  4832.1 1604.66
  4865.3 1599.49  4945.7 1594.28  4975.8 1589.63  4983.0 1587.14  4983.8 1586.34
  5021.5 1586.34  5022.4 1587.14  5025.4 1597.38  5031.2 1599.26  5090.2 1600.25
  5143.5 1599.69  5165.0 1596.66  5192.4 1597.32  5214.7 1598.95  5224.1 1602.15
  5229.8 1602.28  5237.8 1605.71  5245.7 1610.42  5251.4 1610.54  5267.3 1622.88
  5273.0 1623.05  5283.1 1625.94  5288.9 1625.76  5304.7 1629.28  5399.0 1636.57
#Mann=4,-1,0
  4443.6    0.12       0  4832.1    0.05       0  4983.0    0.03       0
  5022.4    0.05       0
Bank Sta=4983,5022.4
Exp/Cntr=0.3,0.1

Type RM Length L Ch R = 1,7216,323,323,323
BEGIN DESCRIPTION:
Long Creek 13.0
END DESCRIPTION:
XS GIS Cut Line= 3
      1628061.42      6925326.39      1628055.00      6926038.00
      1628254.98      6926387.96
#Sta/Elev= 30
  4293.3 1611.76  4350.3 1610.90  4534.9 1607.19  4664.0 1605.94  4774.1 1604.28
  4834.9 1601.90  4904.9 1601.31  4944.9 1595.58  4954.9 1592.46  4957.4 1586.12
  4958.4 1585.32  5001.4 1585.32  5002.5 1586.12  5028.0 1589.70  5040.2 1594.23
  5050.3 1593.87  5062.5 1591.58  5071.9 1591.24  5077.6 1592.13  5093.5 1596.87
  5099.2 1596.72  5108.6 1599.55  5115.1 1603.92  5120.8 1605.11  5130.9 1609.32
  5143.1 1612.16  5158.3 1614.17  5223.8 1617.99  5292.2 1620.08  5408.0 1626.62
#Mann=6,-1,0
  4293.3    0.12       0  4350.3    0.05       0  4664.0    0.12       0
  4774.1    0.05       0  4957.4    0.05       0  5002.5    0.05       0
Bank Sta=4957.4,5002.5
Exp/Cntr=0.3,0.1

Type RM Length L Ch R = 1,6893,435,435,435
BEGIN DESCRIPTION:
Mapping XS 04b7ee21
END DESCRIPTION:
XS GIS Cut Line= 4
      1627960.71      6925368.05      1627801.00      6925697.88
      1627710.72      6926135.38      1628033.63      6926416.62
#Sta/Elev= 30
  4296.6 1610.74  4585.4 1604.64  4665.5 1603.27  4813.9 1598.99  4847.0 1599.16
  4864.1 1597.27  4869.2 1598.44  4887.8 1596.26  4949.1 1594.13  4959.3 1592.80
  4964.7 1589.89  4979.7 1587.89  4980.3 1586.14  4981.2 1585.34  5018.9 1585.34
  5019.8 1586.14  5020.6 1587.59  5030.8 1588.56  5051.2 1593.70  5060.1 1597.62
  5092.0 1600.88  5115.6 1602.08  5121.7 1603.24  5150.2 1602.83  5213.8 1604.97
  5242.3 1604.90  5277.4 1606.37  5334.4 1607.24  5490.1 1612.04  5538.0 1614.69
#Mann=4,-1,0
  4296.6    0.12       0  4585.4    0.05       0  4980.3    0.03       0
  5019.8    0.05       0
Bank Sta=4980.3,5019.8
Exp/Cntr=0.3,0.1

Type RM Length L Ch R = 1,6458,384,384,384
BEGIN DESCRIPTION:
Long Creek 12.0
END DESCRIPTION:
XS GIS Cut Line= 3
      1627282.62      6925533.35      1627360.74      6926034.63
      1627672.07      6926503.79
#Sta/Elev= 30
  4637.9 1631.71  4652.7 1630.06  4662.9 1627.48  4681.9 1622.15  4687.0 1619.22
  4693.2 1617.17  4713.5 1612.47  4743.8 1607.92  4754.9 1604.96  4772.6 1603.18
  4842.0 1600.78  4880.5 1598.18  4885.6 1599.25  4948.4 1597.45  4986.7 1590.68
  4988.2 1585.99  4989.0 1585.19  5026.7 1585.19  5027.7 1585.99  5037.3 1589.21
  5118.3 1589.23  5128.4 1590.41  5158.6 1590.37  5173.3 1592.42  5200.7 1593.41
  5245.3 1598.31  5251.9 1599.79  5287.9 1601.45  5525.5 1605.91  5708.3 1608.11
#Mann=5,-1,0
  4637.9    0.05       0  4772.6    0.12       0  4842.0    0.05       0
  4988.2    0.05       0  5027.7    0.05       0
Bank Sta=4988.2,5027.7
Exp/Cntr=0.3,0.1

Type RM Length L Ch R = 1,6074,516,516,516
BEGIN DESCRIPTION:
Long Creek 11.0
END DESCRIPTION:
XS GIS Cut Line= 3
      1626855.00      6925737.99      1627055.00      6926088.00
      1627685.26      6926572.36
#Sta/Elev= 30
  4590.2 1648.03  4716.2 1646.22  4743.5 1644.17  4781.0 1643.47  4824.2 1639.43
  4861.6 1637.99  4877.4 1635.80  4883.2 1633.53  4912.7 1629.80  4920.6 1628.17
  4926.4 1620.92  4942.2 1615.09  4948.0 1610.49  4958.0 1608.72  4963.8 1602.52
  4979.6 1594.84  4985.0 1580.29  4985.9 1579.49  5023.7 1579.49  5024.6 1580.29
  5029.6 1583.47  5043.8 1587.47  5064.9 1590.65  5100.3 1590.75  5121.1 1592.82
  5150.1 1593.48  5199.9 1598.01  5357.7 1602.03  5478.2 1603.06  5788.2 1608.45
#Mann=3,-1,0
  4590.2    0.05       0  4985.0    0.05       0  5024.6    0.05       0
Bank Sta=4985,5024.6
Exp/Cntr=0.3,0.1