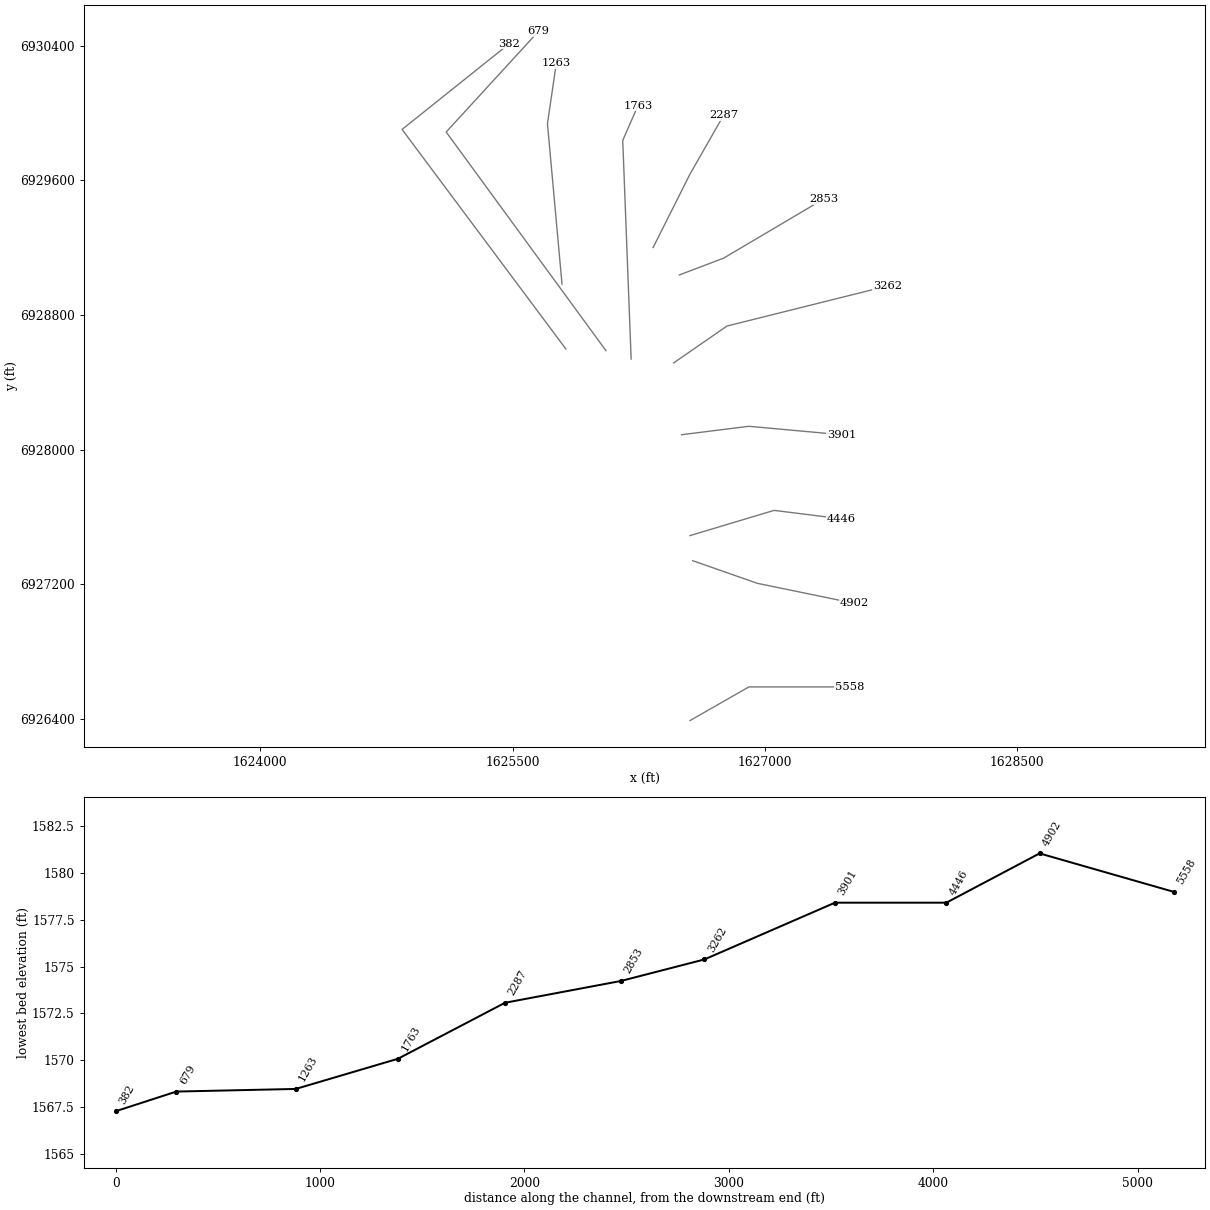
HEC-RAS study Long Creek.prj: Long Creek Base Level Engineering

--- Long Creek.g01 (geometry) --- (continued)

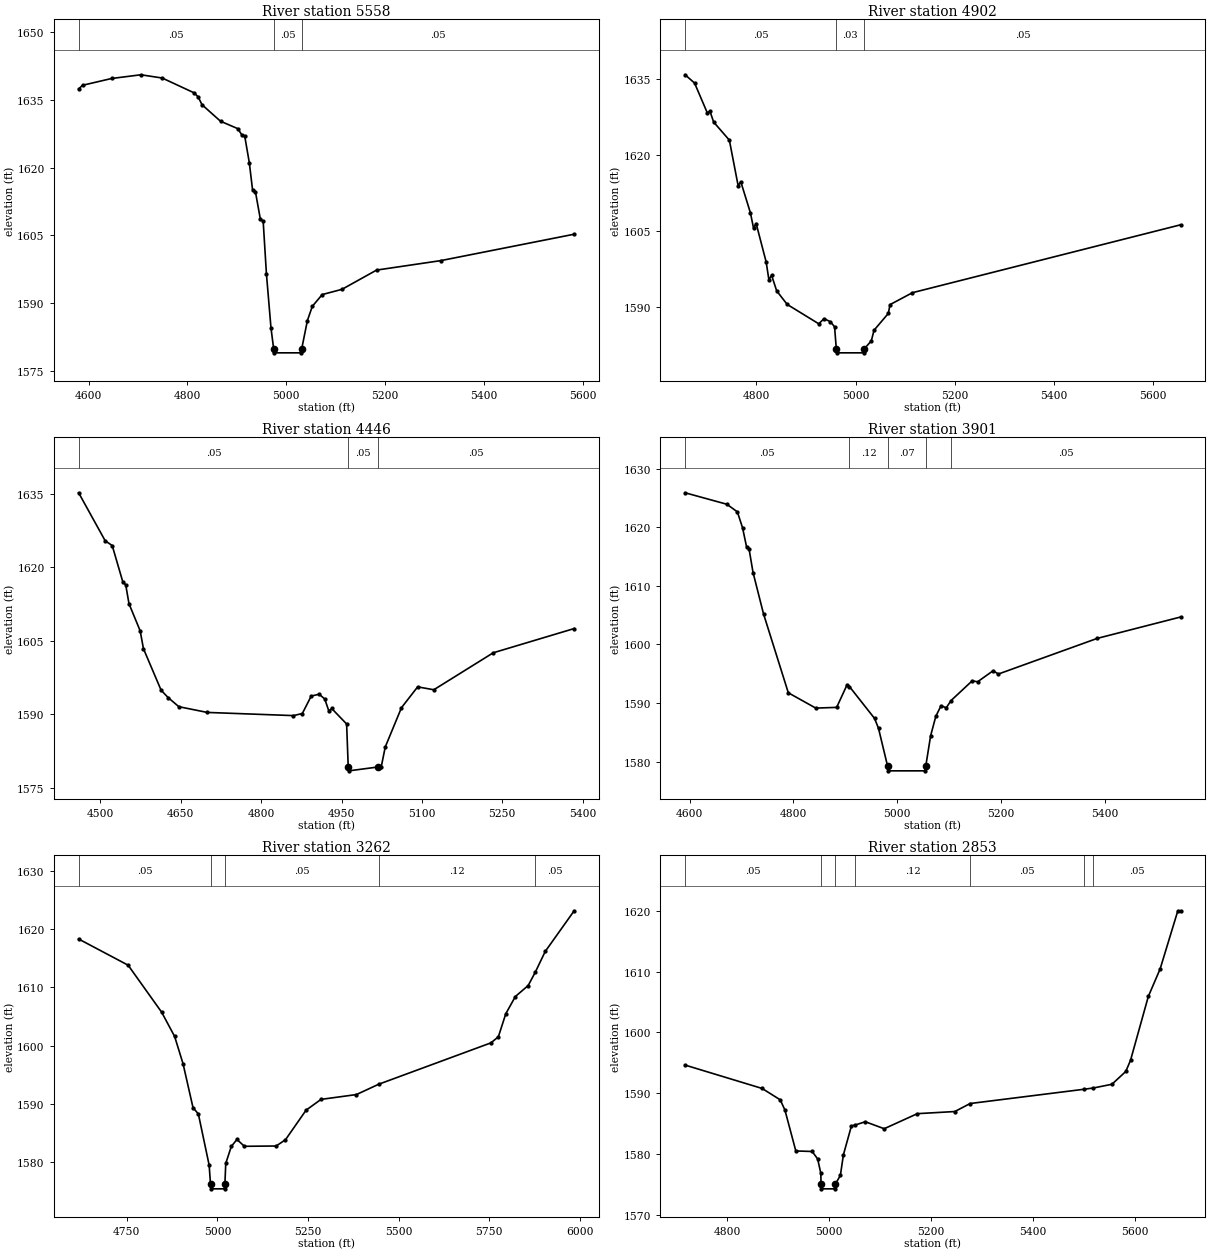
Type RM Length L Ch R = 1,5558,656,656,656
BEGIN DESCRIPTION:
Long Creek 10.0
END DESCRIPTION:
XS GIS Cut Line= 3
      1626555.01      6926388.00      1626905.00      6926588.00
      1627505.00      6926588.00
#Sta/Elev= 30
  4580.0 1637.45  4587.9 1638.26  4646.9 1639.77  4706.0 1640.59  4749.2 1639.87
  4813.9 1636.58  4821.9 1635.69  4829.8 1633.95  4867.2 1630.30  4902.5 1628.64
  4910.4 1627.24  4916.2 1627.00  4925.5 1621.12  4932.0 1615.15  4937.8 1614.73
  4947.8 1608.64  4953.6 1608.09  4960.1 1596.56  4969.4 1584.47  4974.9 1579.79
  4976.2 1578.99  5030.1 1578.99  5031.4 1579.79  5043.1 1586.15  5053.1 1589.31
  5073.1 1591.90  5113.1 1593.06  5183.1 1597.32  5313.1 1599.42  5583.1 1605.27
#Mann=3,-1,0
  4580.0    0.05       0  4974.9    0.05       0  5031.4    0.05       0
Bank Sta=4974.9,5031.4
Exp/Cntr=0.3,0.1

Type RM Length L Ch R = 1,4902,456,456,456
BEGIN DESCRIPTION:
Long Creek 9.0
END DESCRIPTION:
XS GIS Cut Line= 3
      1626570.78      6927338.90      1626954.93      6927204.34
      1627534.33      6927084.98
#Sta/Elev= 30
  4656.5 1635.74  4675.6 1634.11  4701.3 1628.23  4706.6 1628.58  4714.0 1626.44
  4745.7 1622.88  4763.4 1613.91  4768.7 1614.71  4788.1 1608.59  4794.4 1605.59
  4799.7 1606.47  4819.9 1598.90  4825.4 1595.39  4830.7 1596.32  4841.1 1593.22
  4862.3 1590.56  4925.9 1586.75  4936.5 1587.77  4949.5 1587.15  4957.7 1586.16
  4961.2 1581.84  4962.4 1581.04  5016.4 1581.04  5017.7 1581.84  5031.8 1583.40
  5037.2 1585.48  5066.1 1588.80  5069.4 1590.52  5114.6 1592.87  5655.1 1606.23
#Mann=3,-1,0
  4656.5    0.05       0  4961.2    0.03       0  5017.7    0.05       0
Bank Sta=4961.2,5017.7
Exp/Cntr=0.3,0.1

Type RM Length L Ch R = 1,4446,545,545,545
BEGIN DESCRIPTION:
Long Creek 8.0
END DESCRIPTION:
XS GIS Cut Line= 3
      1626554.98      6927488.00      1627055.00      6927638.00
      1627454.96      6927588.01
#Sta/Elev= 30
  4459.2 1635.20  4508.8 1625.39  4521.9 1624.42  4541.9 1616.92  4547.1 1616.42
  4553.2 1612.55  4574.1 1606.99  4580.2 1603.36  4613.2 1594.87  4626.3 1593.37
  4646.3 1591.51  4699.3 1590.34  4860.3 1589.69  4876.8 1590.12  4893.4 1593.68
  4908.2 1594.06  4918.6 1593.09  4926.4 1590.61  4931.6 1591.15  4959.5 1587.98
  4962.5 1579.21  4963.8 1578.41  5019.0 1579.21  5024.1 1579.21  5031.6 1583.28
  5061.9 1591.31  5092.1 1595.56  5122.3 1594.97  5233.2 1602.52  5384.3 1607.47
#Mann=3,-1,0
  4459.2    0.05       0  4962.5    0.05       0  5019.0    0.05       0
Bank Sta=4962.5,5019
Exp/Cntr=0.3,0.1

Type RM Length L Ch R = 1,3901,639,639,639
BEGIN DESCRIPTION:
Long Creek 7.0
END DESCRIPTION:
XS GIS Cut Line= 3
      1626505.01      6928088.00      1626905.00      6928138.00
      1627455.03      6928088.00
#Sta/Elev= 30
  4591.1 1625.87  4671.7 1623.91  4691.9 1622.61  4701.9 1619.89  4709.5 1616.68
  4714.5 1616.24  4722.1 1612.26  4742.3 1605.20  4790.1 1591.73  4843.0 1589.12
  4883.3 1589.24  4903.5 1593.12  4908.0 1592.79  4956.4 1587.35  4964.0 1585.66
  4981.5 1579.21  4983.2 1578.41  5053.4 1578.41  5055.1 1579.21  5064.5 1584.41
  5074.5 1587.72  5084.6 1589.53  5094.6 1589.17  5103.8 1590.40  5144.8 1593.79
  5154.9 1593.60  5185.0 1595.50  5195.0 1594.93  5385.8 1601.02  5546.5 1604.67
#Mann=5,-1,0
  4591.1    0.05       0  4908.0    0.12       0  4981.5    0.07       0
  5055.1    0.12       0  5103.8    0.05       0
Bank Sta=4981.5,5055.1
Exp/Cntr=0.3,0.1

Type RM Length L Ch R = 1,3262,409,409,409
BEGIN DESCRIPTION:
Long Creek 6.0
END DESCRIPTION:
XS GIS Cut Line= 3
      1626457.97      6928515.10      1626774.81      6928734.28
      1627728.10      6928972.19
#Sta/Elev= 30
  4616.9 1618.31  4753.5 1613.81  4846.1 1605.73  4881.9 1601.56  4905.1 1596.88
  4932.6 1589.34  4947.4 1588.24  4977.2 1579.44  4980.9 1576.18  4981.8 1575.38
  5019.7 1575.38  5020.6 1576.18  5023.0 1579.75  5038.3 1582.66  5053.9 1583.87
  5074.4 1582.69  5162.1 1582.74  5187.9 1583.82  5244.6 1588.89  5285.9 1590.75
  5383.7 1591.58  5445.0 1593.35  5754.8 1600.46  5775.4 1601.50  5796.0 1605.47
  5822.3 1608.42  5857.8 1610.32  5877.4 1612.61  5904.8 1616.17  5984.7 1623.16
#Mann=5,-1,0
  4616.9    0.05       0  4980.9    0.05       0  5020.6    0.05       0
  5445.0    0.12       0  5877.4    0.05       0
Bank Sta=4980.9,5020.6
Exp/Cntr=0.3,0.1

Type RM Length L Ch R = 1,2853,566,566,566
BEGIN DESCRIPTION:
Long Creek 5.0
END DESCRIPTION:
XS GIS Cut Line= 3
      1626491.93      6929038.14      1626755.00      6929138.00
      1627349.58      6929489.53
#Sta/Elev= 30
  4717.3 1594.61  4868.4 1590.76  4903.9 1588.89  4913.1 1587.21  4934.5 1580.47
  4966.6 1580.38  4977.3 1579.16  4983.6 1576.77  4983.9 1575.03  4984.5 1574.23
  5011.6 1574.23  5012.2 1575.03  5021.9 1576.44  5027.9 1579.85  5043.6 1584.59
  5050.2 1584.72  5070.8 1585.28  5107.9 1584.13  5172.9 1586.61  5246.4 1586.96
  5276.5 1588.28  5500.0 1590.63  5518.4 1590.84  5554.6 1591.45  5581.8 1593.56
  5591.1 1595.40  5626.0 1605.91  5649.2 1610.45  5683.9 1620.02  5689.4 1620.02
#Mann=7,-1,0
  4717.3    0.05       0  4983.9    0.03       0  5012.2    0.05       0
  5050.2    0.12       0  5276.5    0.05       0  5500.0    0.12       0
  5518.4    0.05       0
Bank Sta=4983.9,5012.2
Exp/Cntr=0.3,0.1

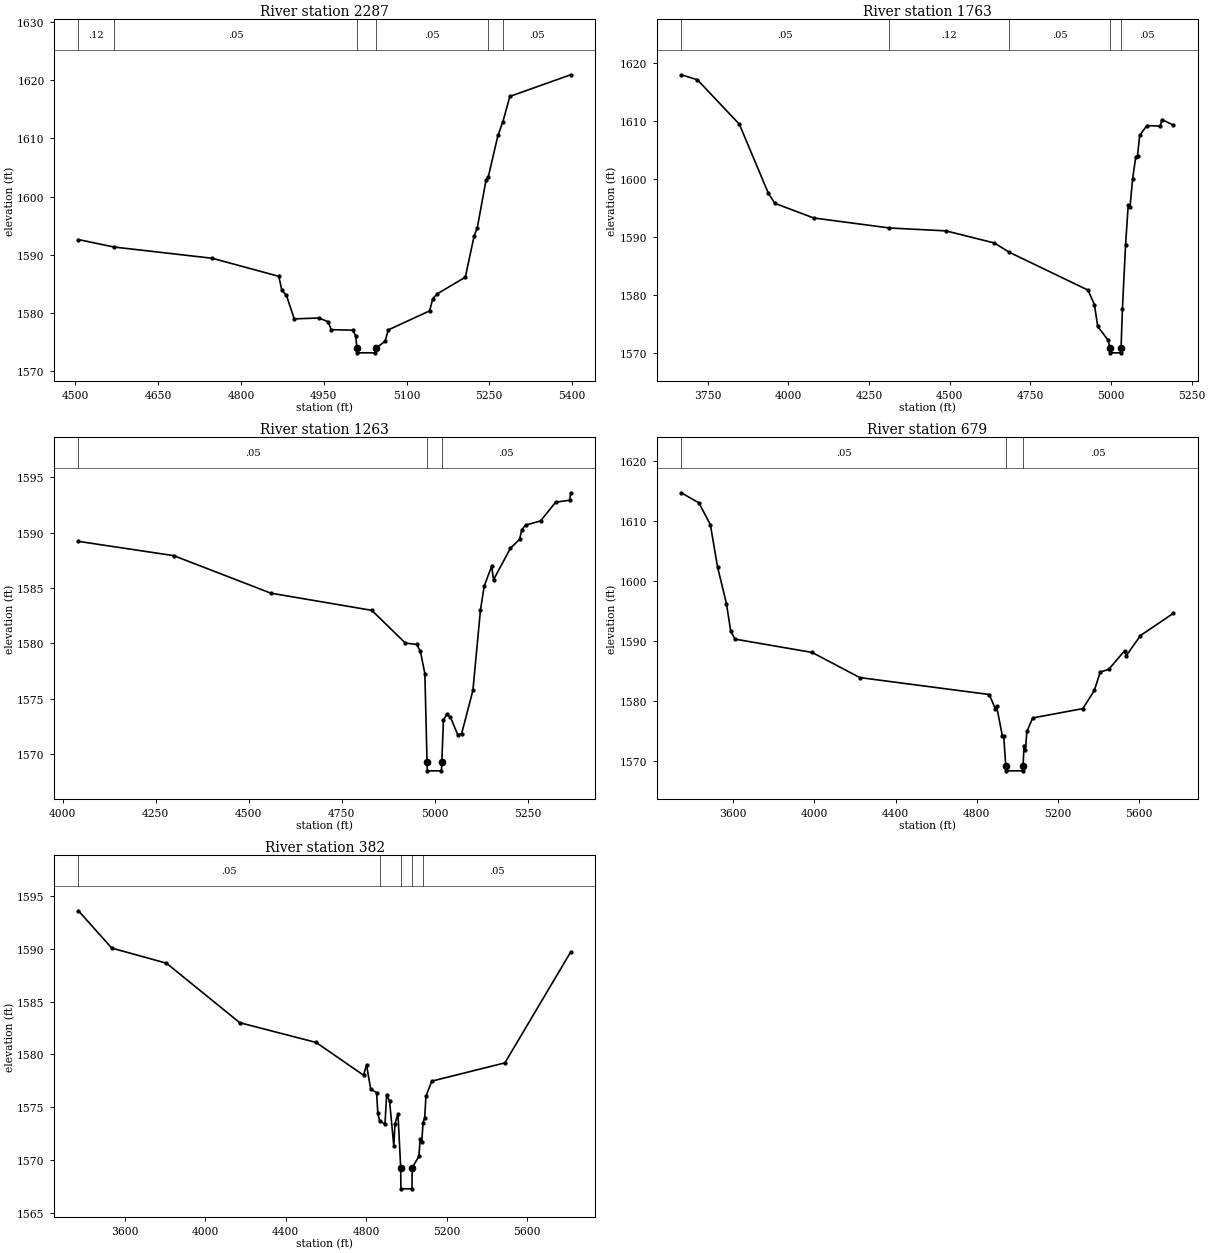
Type RM Length L Ch R = 1,2287,524,524,524
BEGIN DESCRIPTION:
Long Creek 4.0
END DESCRIPTION:
XS GIS Cut Line= 3
      1626335.74      6929201.39      1626555.00      6929638.00
      1626755.01      6929988.02
#Sta/Elev= 30
  4505.7 1592.58  4569.8 1591.30  4748.1 1589.36  4868.6 1586.25  4874.2 1583.85
  4882.4 1582.99  4896.6 1578.92  4941.2 1579.07  4958.0 1578.44  4963.6 1577.06
  5002.2 1576.98  5007.9 1576.02  5010.2 1573.87  5011.0 1573.07  5043.4 1573.07
  5044.2 1573.87  5061.2 1575.05  5067.0 1577.02  5141.8 1580.30  5147.6 1582.39
  5155.5 1583.23  5206.6 1586.10  5222.5 1593.22  5228.2 1594.60  5244.1 1602.84
  5248.1 1603.36  5265.7 1610.54  5274.6 1612.88  5287.2 1617.24  5397.4 1620.97
#Mann=6,-1,0
  4505.7    0.12       0  4569.8    0.05       0  5010.2    0.05       0
  5044.2    0.05       0  5248.1    0.12       0  5274.6    0.05       0
Bank Sta=5010.2,5044.2
Exp/Cntr=0.3,0.1

Type RM Length L Ch R = 1,1763,500,500,500
BEGIN DESCRIPTION:
Long Creek 3.0
END DESCRIPTION:
XS GIS Cut Line= 3
      1626205.00      6928538.01      1626155.00      6929838.00
      1626244.99      6930044.06
#Sta/Elev= 30
  3667.6 1618.05  3717.6 1617.19  3847.7 1609.52  3937.8 1597.58  3957.8 1595.87
  4077.9 1593.35  4313.0 1591.62  4488.2 1591.12  4638.3 1589.03  4684.5 1587.43
  4928.5 1580.90  4948.5 1578.37  4958.5 1574.64  4990.4 1572.30  4996.9 1570.88
  4997.7 1570.08  5030.1 1570.08  5030.9 1570.88  5035.2 1577.70  5044.9 1588.70
  5053.2 1595.55  5058.7 1595.19  5066.8 1600.12  5076.6 1603.90  5082.1 1604.12
  5088.6 1607.58  5110.9 1609.28  5152.3 1609.20  5157.7 1610.32  5193.4 1609.36
#Mann=5,-1,0
  3667.6    0.05       0  4313.0    0.12       0  4684.5    0.05       0
  4996.9    0.05       0  5030.9    0.05       0
Bank Sta=4996.9,5030.9
Exp/Cntr=0.3,0.1

Type RM Length L Ch R = 1,1263,584,584,584
BEGIN DESCRIPTION:
Long Creek 2.0
END DESCRIPTION:
XS GIS Cut Line= 3
      1625793.90      6928983.01      1625707.25      6929937.46
      1625760.03      6930297.95
#Sta/Elev= 30
  4042.5 1589.20  4298.5 1587.91  4559.6 1584.52  4830.7 1582.97  4921.1 1580.01
  4951.2 1579.89  4961.2 1579.30  4973.4 1577.24  4979.2 1569.27  4980.1 1568.47
  5018.0 1568.47  5018.9 1569.27  5023.3 1573.04  5031.7 1573.57  5041.8 1573.34
  5062.1 1571.71  5072.2 1571.83  5102.5 1575.74  5122.7 1582.97  5132.8 1585.16
  5152.9 1586.96  5158.0 1585.74  5203.5 1588.59  5227.9 1589.38  5233.9 1590.26
  5244.0 1590.67  5284.4 1591.05  5324.8 1592.74  5362.6 1592.92  5365.2 1593.59
#Mann=3,-1,0
  4042.5    0.05       0  4979.2    0.05       0  5018.9    0.05       0
Bank Sta=4979.2,5018.9
Exp/Cntr=0.3,0.1

Type RM Length L Ch R = 1,679,297,297,297
BEGIN DESCRIPTION:
Long Creek 1.0
END DESCRIPTION:
XS GIS Cut Line= 3
      1626054.98      6928588.03      1625105.00      6929888.00
      1625654.98      6930487.98
#Sta/Elev= 30
  3344.5 1614.75  3431.2 1613.07  3487.7 1609.45  3523.2 1602.37  3567.2 1596.22
  3588.1 1591.64  3609.0 1590.32  3988.5 1588.10  4223.8 1583.90  4861.5 1581.07
  4890.9 1578.70  4897.1 1579.18  4926.4 1574.08  4932.6 1574.13  4942.7 1569.13
  4944.7 1568.33  5026.0 1568.33  5027.9 1569.13  5032.6 1572.55  5039.4 1571.89
  5046.8 1574.90  5075.1 1577.16  5322.4 1578.72  5379.1 1581.77  5407.5 1584.80
  5450.0 1585.29  5527.7 1588.37  5535.1 1587.50  5605.7 1590.91  5768.5 1594.64
#Mann=3,-1,0
  3344.5    0.05       0  4942.7    0.05       0  5027.9    0.05       0
Bank Sta=4942.7,5027.9
Exp/Cntr=0.3,0.1

Type RM Length L Ch R = 1,382,0,0,0
BEGIN DESCRIPTION:
Long Creek 0.0
END DESCRIPTION:
XS GIS Cut Line= 3
      1625816.76      6928597.70      1624842.64      6929903.61
      1625479.99      6930413.00
#Sta/Elev= 30
  3370.8 1593.59  3536.1 1590.06  3807.8 1588.63  4172.0 1583.00  4551.5 1581.13
  4787.1 1578.03  4801.7 1579.03  4822.5 1576.71  4851.7 1576.39  4858.0 1574.42
  4866.3 1573.73  4893.4 1573.40  4901.8 1576.20  4916.4 1575.55  4937.2 1571.35
  4943.4 1573.44  4958.0 1574.39  4971.5 1569.28  4972.5 1567.28  5027.5 1567.28
  5028.5 1569.28  5061.9 1570.34  5068.3 1572.00  5076.3 1571.73  5082.6 1573.55
  5090.7 1573.99  5097.1 1576.05  5125.9 1577.47  5489.3 1579.20  5815.9 1589.69
#Mann=5,-1,0
  3370.8    0.05       0  4866.3    0.12       0  4971.5    0.07       0
  5028.5    0.12       0  5082.6    0.05       0
Bank Sta=4971.5,5028.5
Exp/Cntr=0.3,0.1

Chan Stop Cuts=-1