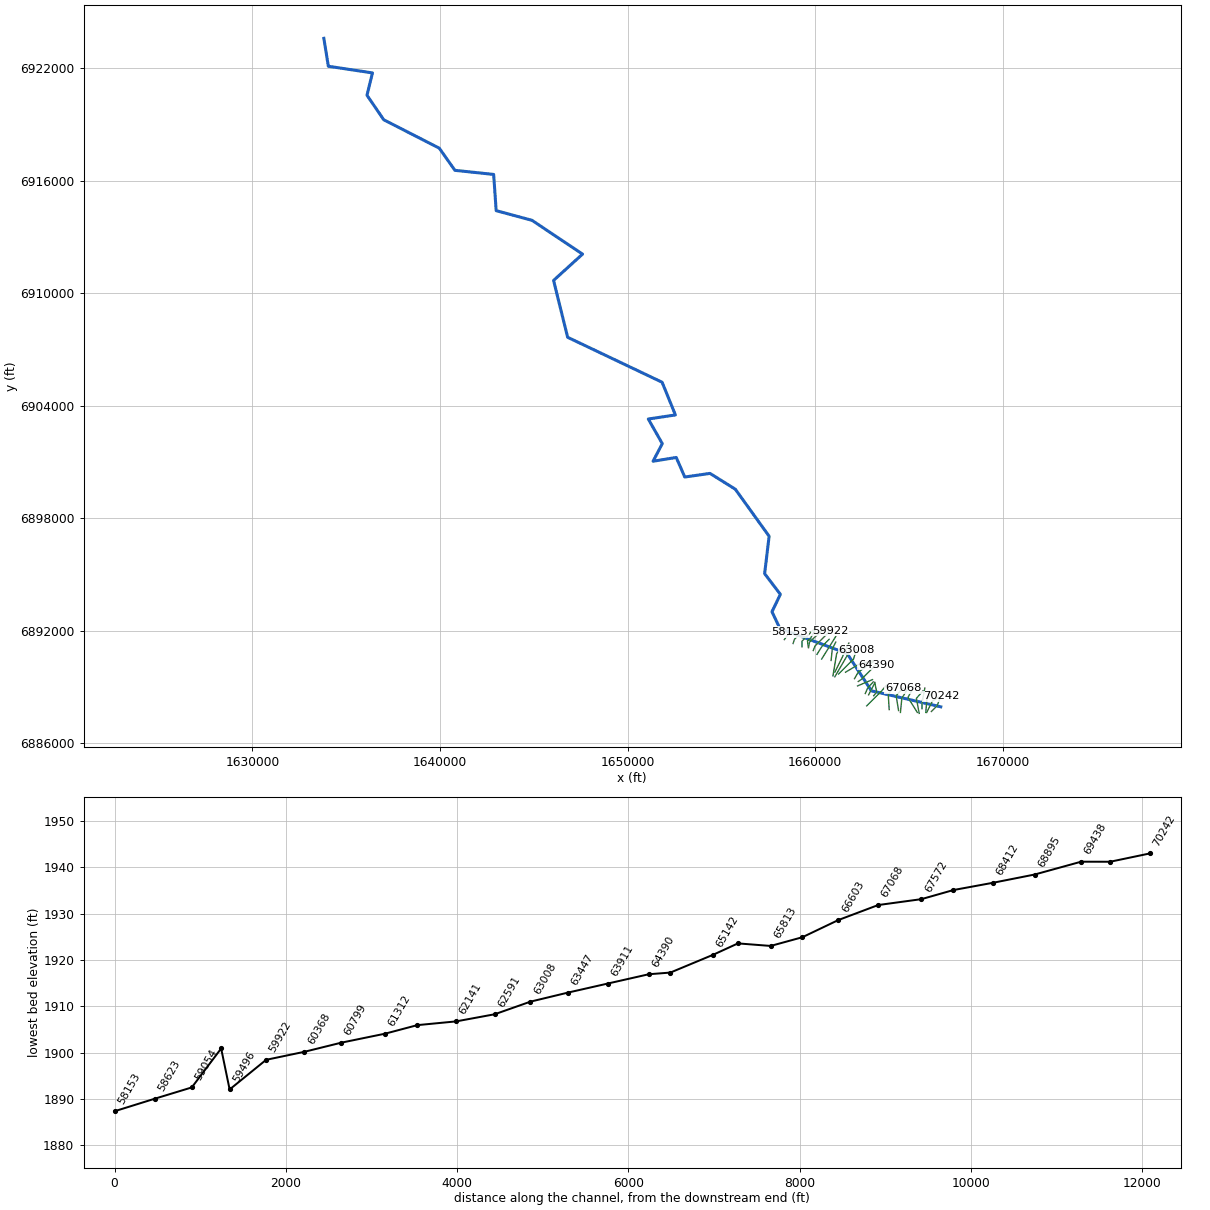
--- South Prong Long Creek.prj (project) ---

Proj Title=South Prong Long Creek Base Level Engineering
Current Plan=p01
Default Exp/Contr=0.3,0.1
English Units
Geom File=g01
Flow File=f01
Plan File=p01
Y Axis Title=Elevation
X Axis Title(PF)=Main Channel Distance
X Axis Title(XS)=Station
BEGIN DESCRIPTION:
South Prong Long Creek
END DESCRIPTION:
DSS Export Rating Curves= 0
DSS Export Rating Curve Sorted= 0
DSS Export Volume Flow Curves= 0
DXF OffsetX= 0
DXF OffsetY= 0
DXF ScaleX= 1
DXF ScaleY= 10

--- South Prong Long Creek.p01 (plan) ---

Plan Title=Multiple Run
Short Identifier=Multiple
Geom File=g01
Flow File=f01
Subcritical Flow
K Sum by GR= 0
Std Step Tol= 0.01
Critical Tol= 0.01
Num of Std Step Trials= 20
Max Error Tol= 0.3
Flow Tol Ratio= 0.001
Split Flow NTrial= 30
Split Flow Tol= 0.02
Split Flow Ratio= 0.02
Log Output Level= 0
Friction Slope Method= 1
Unsteady Friction Slope Method= 2
Unsteady Bridges Friction Slope Method= 1
Parabolic Critical Depth
Global Vel Dist=  1 , 1 , 1
Global Log Level= 0
CheckData=True
Encroach Param= -1, 0, 0, 0
BEGIN DESCRIPTION:
Multiple Run
END DESCRIPTION:

--- South Prong Long Creek.f01 (steady flow) ---

Flow Title=Multiple
Number of Profiles=7
Profile Names=10-year,25-year,50-year,1pct_min,100-year,1pct_plu,500-year
River Rch & RM= South Prong Long,Reach-1,70242
     322     448     552     339     676    1350    1027
River Rch & RM= South Prong Long,Reach-1,60799
     335     466     574     352     702    1401    1065
River Rch & RM= South Prong Long,Reach-1,55925
     438     618     770     476     949    1894    1465
River Rch & RM= South Prong Long,Reach-1,51344
     472     668     833     516    1029    2054    1594
River Rch & RM= South Prong Long,Reach-1,50389
     652     937    1181     738    1473    2939    2324
River Rch & RM= South Prong Long,Reach-1,45627
     690     991    1248     780    1556    3105    2452
River Rch & RM= South Prong Long,Reach-1,36272
     767    1107    1398     876    1748    3489    2771
River Rch & RM= South Prong Long,Reach-1,30299
     823    1191    1507     945    1886    3763    2996
River Rch & RM= South Prong Long,Reach-1,22690
     904    1313    1667    1049    2093    4177    3345
River Rch & RM= South Prong Long,Reach-1,17427
     956    1394    1774    1119    2233    4456    3587
River Rch & RM= South Prong Long,Reach-1,13145
    1281    1891    2427    1543    3078    6142    5020
River Rch & RM= South Prong Long,Reach-1,12229
    1343    1987    2553    1625    3242    6468    5299
River Rch & RM= South Prong Long,Reach-1,9427
    1397    2071    2665    1699    3390    6764    5559
River Rch & RM= South Prong Long,Reach-1,3395
    1590    2367    3056    1953    3897    7776    6426
Boundary for River Rch & Prof#=South Prong Long,Reach-1,1
Up Type=0
Dn Type=3
Dn Slope=0.005
Boundary for River Rch & Prof#=South Prong Long,Reach-1,2
Up Type=0
Dn Type=3
Dn Slope=0.005
Boundary for River Rch & Prof#=South Prong Long,Reach-1,3
Up Type=0
Dn Type=3
Dn Slope=0.005
Boundary for River Rch & Prof#=South Prong Long,Reach-1,4
Up Type=0
Dn Type=3
Dn Slope=0.005
Boundary for River Rch & Prof#=South Prong Long,Reach-1,5
Up Type=0
Dn Type=3
Dn Slope=0.005
Boundary for River Rch & Prof#=South Prong Long,Reach-1,6
Up Type=0
Dn Type=3
Dn Slope=0.005
Boundary for River Rch & Prof#=South Prong Long,Reach-1,7
Up Type=0
Dn Type=3
Dn Slope=0.005

--- South Prong Long Creek.g01 (geometry) ---

Geom Title=Existing Conditions

River Reach=South Prong Long,Reach-1
Reach XY= 30
      1666705.00      6887938.00      1663006.63      6888791.09
      1661711.19      6890780.25      1658128.01      6892114.53
      1657704.64      6893008.21      1658151.47      6893936.55
      1657312.31      6895037.90      1657551.50      6897036.55
      1655747.00      6899544.33      1654399.06      6900385.74
      1653052.70      6900193.06      1652599.12      6901236.04
      1651362.79      6901034.57      1651854.92      6901972.60
      1651108.08      6903286.32      1652554.49      6903503.21
      1651844.24      6905247.68      1646807.50      6907644.03
      1646056.05      6910677.56      1647601.63      6912079.85
      1644907.29      6913882.15      1642995.21      6914398.52
      1642861.06      6916329.86      1640795.21      6916548.51
      1639961.19      6917730.19      1636998.81      6919245.81
      1636105.52      6920553.22      1636397.20      6921744.21
      1634045.00      6922098.63      1633805.00      6923588.00

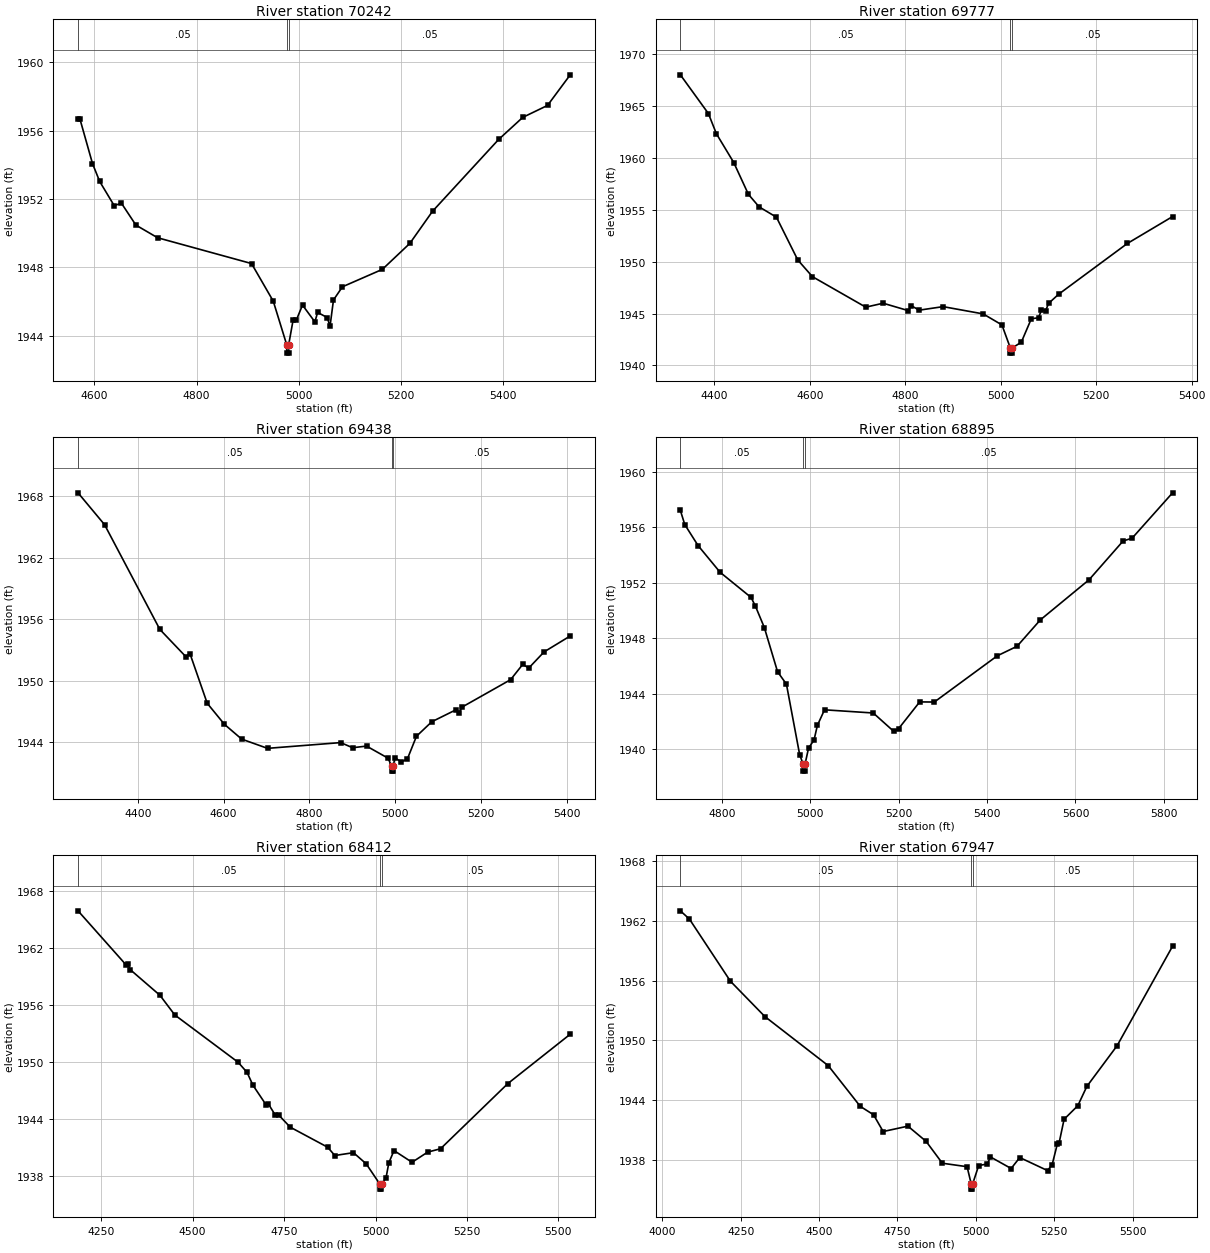
Type RM Length L Ch R = 1,70242,465,465,465
BEGIN DESCRIPTION:
South Prong Long Creek 133.0
END DESCRIPTION:
XS GIS Cut Line= 3
      1666204.99      6887687.99      1666505.00      6887988.00
      1666705.00      6888488.00
#Sta/Elev= 30
  4568.1 1956.70  4571.7 1956.70  4596.4 1954.08  4610.5 1953.03  4638.8 1951.62
  4653.0 1951.76  4681.3 1950.48  4723.7 1949.74  4907.5 1948.23  4950.0 1946.03
  4976.2 1943.49  4976.5 1942.99  4980.0 1942.99  4980.2 1943.49  4988.8 1944.92
  4995.1 1944.92  5007.2 1945.80  5031.4 1944.82  5036.8 1945.37  5055.7 1945.07
  5061.0 1944.55  5067.8 1946.10  5085.3 1946.87  5163.4 1947.89  5217.2 1949.41
  5261.6 1951.29  5390.9 1955.49  5438.0 1956.78  5486.5 1957.48  5530.9 1959.27
#Mann=3,-1,0
  4568.1    0.05       0  4976.2    0.03       0  4980.2    0.05       0
Bank Sta=4976.2,4980.2
Exp/Cntr=0.3,0.1

Type RM Length L Ch R = 1,69777,339,339,339
BEGIN DESCRIPTION:
South Prong Long Creek 132.0
END DESCRIPTION:
XS GIS Cut Line= 3
      1665954.99      6887637.99      1666255.00      6888238.00
      1666555.01      6888438.01
#Sta/Elev= 30
  4328.6 1968.01  4387.3 1964.28  4404.1 1962.33  4440.4 1959.56  4471.2 1956.49
  4493.5 1955.29  4529.9 1954.29  4574.6 1950.17  4605.3 1948.56  4717.1 1945.62
  4753.5 1946.00  4806.6 1945.28  4812.2 1945.77  4828.9 1945.33  4879.2 1945.67
  4963.1 1944.97  5002.4 1943.91  5020.0 1941.69  5020.2 1941.19  5023.7 1941.19
  5024.0 1941.69  5043.0 1942.24  5064.0 1944.50  5079.1 1944.60  5085.1 1945.32
  5094.1 1945.28  5100.1 1945.98  5121.1 1946.86  5265.3 1951.76  5360.0 1954.35
#Mann=3,-1,0
  4328.6    0.05       0  5020.0    0.05       0  5024.0    0.05       0
Bank Sta=5020,5024
Exp/Cntr=0.3,0.1

Type RM Length L Ch R = 1,69438,543,543,543
BEGIN DESCRIPTION:
South Prong Long Creek 131.0
END DESCRIPTION:
XS GIS Cut Line= 3
      1665905.00      6887638.05      1665968.29      6888374.64
      1666247.78      6888671.60
#Sta/Elev= 30
  4260.7 1968.32  4322.5 1965.22  4451.4 1955.01  4511.6 1952.37  4521.6 1952.65
  4561.8 1947.81  4601.9 1945.76  4642.1 1944.32  4702.3 1943.42  4872.9 1943.98
  4900.6 1943.48  4933.1 1943.64  4983.3 1942.46  4991.3 1941.70  4991.5 1941.20
  4995.1 1941.20  4995.4 1941.70  4999.2 1942.51  5014.3 1942.09  5028.4 1942.40
  5049.5 1944.60  5085.1 1946.01  5141.7 1947.18  5148.6 1946.88  5155.7 1947.44
  5268.8 1950.11  5297.1 1951.60  5311.3 1951.25  5346.9 1952.82  5407.8 1954.37
#Mann=3,-1,0
  4260.7    0.05       0  4991.3    0.03       0  4995.4    0.05       0
Bank Sta=4991.3,4995.4
Exp/Cntr=0.3,0.1

Type RM Length L Ch R = 1,68895,483,483,483
BEGIN DESCRIPTION:
South Prong Long Creek 130.0
END DESCRIPTION:
XS GIS Cut Line= 3
      1665705.00      6887838.05      1665705.00      6888138.00
      1665855.00      6888938.01
#Sta/Elev= 30
  4705.8 1957.22  4715.8 1956.20  4745.8 1954.69  4795.8 1952.76  4865.8 1950.95
  4875.8 1950.31  4895.8 1948.78  4925.8 1945.59  4945.8 1944.70  4975.8 1939.61
  4983.7 1938.93  4984.0 1938.43  4987.6 1938.43  4987.9 1938.93  4995.8 1940.08
  5008.3 1940.68  5015.9 1941.73  5032.0 1942.85  5142.3 1942.62  5188.9 1941.29
  5199.9 1941.50  5247.4 1943.42  5280.5 1943.41  5422.9 1946.74  5467.8 1947.43
  5520.4 1949.33  5630.6 1952.22  5707.8 1955.02  5728.1 1955.22  5819.7 1958.49
#Mann=3,-1,0
  4705.8    0.05       0  4983.7    0.05       0  4987.9    0.05       0
Bank Sta=4983.7,4987.9
Exp/Cntr=0.3,0.1

Type RM Length L Ch R = 1,68412,465,465,465
BEGIN DESCRIPTION:
South Prong Long Creek 129.0
END DESCRIPTION:
XS GIS Cut Line= 3
      1665555.00      6887587.98      1665405.00      6888388.00
      1665755.02      6888788.02
#Sta/Elev= 30
  4186.8 1965.89  4318.2 1960.21  4323.3 1960.28  4329.3 1959.72  4410.7 1957.02
  4451.4 1954.95  4624.3 1949.99  4648.9 1948.92  4665.0 1947.57  4701.5 1945.48
  4706.6 1945.64  4726.1 1944.43  4736.2 1944.41  4766.8 1943.17  4869.3 1941.06
  4888.8 1940.19  4939.7 1940.49  4974.5 1939.32  5012.4 1937.16  5012.7 1936.66
  5016.3 1936.66  5016.6 1937.16  5028.8 1937.85  5036.4 1939.42  5050.6 1940.71
  5099.9 1939.48  5142.7 1940.55  5177.8 1940.90  5361.9 1947.75  5532.3 1952.93
#Mann=3,-1,0
  4186.8    0.05       0  5012.4    0.05       0  5016.6    0.05       0
Bank Sta=5012.4,5016.6
Exp/Cntr=0.3,0.1

Type RM Length L Ch R = 1,67947,375,375,375
BEGIN DESCRIPTION:
South Prong Long Creek 128.0
END DESCRIPTION:
XS GIS Cut Line= 3
      1665455.01      6887637.99      1664955.00      6888438.00
      1665254.99      6888987.99
#Sta/Elev= 30
  4057.6 1963.01  4086.5 1962.18  4217.4 1955.94  4327.1 1952.40  4529.3 1947.47
  4631.3 1943.39  4673.8 1942.54  4704.4 1940.86  4783.4 1941.40  4841.2 1939.88
  4893.1 1937.68  4972.1 1937.33  4985.4 1935.58  4985.6 1935.08  4989.3 1935.08
  4989.6 1935.58  5009.1 1937.45  5036.6 1937.60  5046.6 1938.31  5112.6 1937.15
  5140.1 1938.25  5228.8 1936.94  5243.5 1937.55  5259.7 1939.58  5265.4 1939.69
  5281.5 1942.09  5325.2 1943.45  5354.1 1945.39  5450.5 1949.47  5627.5 1959.46
#Mann=3,-1,0
  4057.6    0.05       0  4985.4    0.03       0  4989.6    0.05       0
Bank Sta=4985.4,4989.6
Exp/Cntr=0.3,0.1

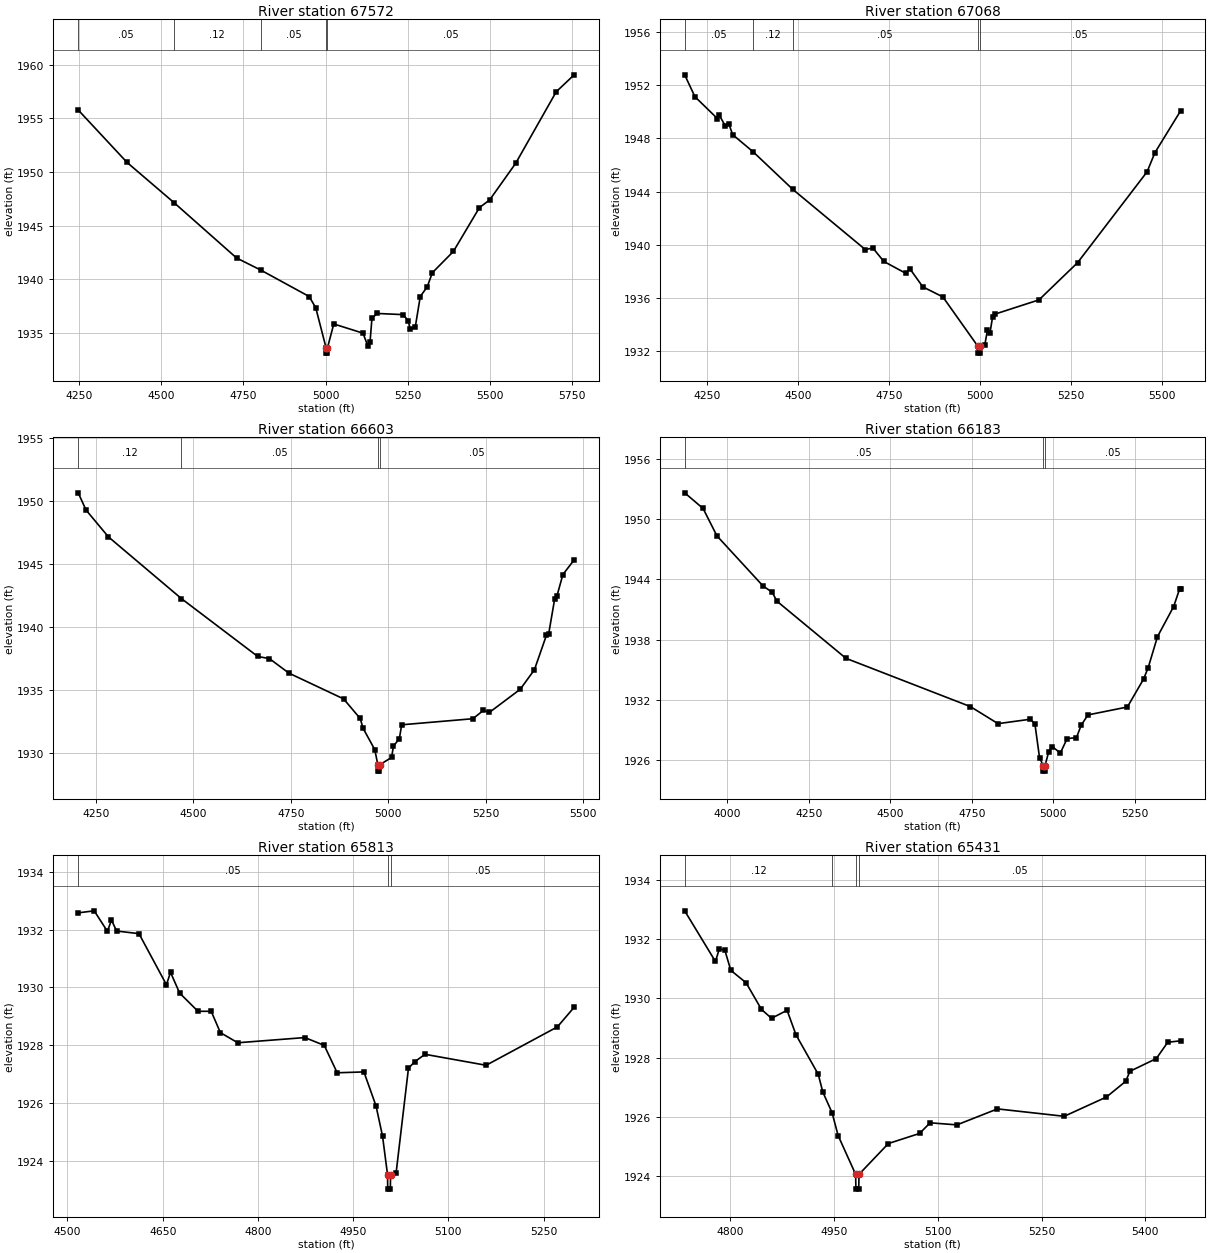
Type RM Length L Ch R = 1,67572,504,504,504
BEGIN DESCRIPTION:
South Prong Long Creek 127.0
END DESCRIPTION:
XS GIS Cut Line= 3
      1664555.00      6887637.97      1664629.39      6888387.69
      1665022.88      6889034.62
#Sta/Elev= 30
  4246.6 1955.78  4395.4 1950.89  4538.5 1947.14  4729.0 1941.98  4802.3 1940.86
  4950.1 1938.39  4970.2 1937.33  5001.5 1933.61  5001.8 1933.11  5005.6 1933.11
  5005.9 1933.61  5025.0 1935.83  5114.1 1934.97  5129.1 1933.75  5135.4 1934.12
  5141.3 1936.35  5156.7 1936.81  5236.2 1936.70  5251.7 1936.14  5257.9 1935.35
  5273.0 1935.50  5288.5 1938.39  5309.8 1939.30  5325.3 1940.61  5389.3 1942.59
  5468.7 1946.68  5499.7 1947.39  5579.1 1950.81  5702.6 1957.48  5757.2 1959.06
#Mann=5,-1,0
  4246.6    0.05       0  4538.5    0.12       0  4802.3    0.05       0
  5001.5    0.03       0  5005.9    0.05       0
Bank Sta=5001.5,5005.9
Exp/Cntr=0.3,0.1

Type RM Length L Ch R = 1,67068,465,465,465
BEGIN DESCRIPTION:
South Prong Long Creek 126.0
END DESCRIPTION:
XS GIS Cut Line= 3
      1664455.00      6887738.02      1664325.03      6888537.93
      1664705.03      6888938.03
#Sta/Elev= 30
  4189.6 1952.79  4217.8 1951.14  4279.4 1949.50  4284.5 1949.76  4301.0 1948.95
  4311.2 1949.08  4321.3 1948.29  4378.2 1946.98  4486.0 1944.18  4686.0 1939.63
  4706.3 1939.76  4736.7 1938.74  4797.5 1937.84  4807.6 1938.21  4843.7 1936.83
  4898.8 1936.07  4995.3 1932.34  4995.6 1931.84  4999.5 1931.84  4999.8 1932.34
  5014.0 1932.48  5021.3 1933.57  5028.2 1933.37  5035.4 1934.57  5042.3 1934.78
  5162.8 1935.85  5268.8 1938.65  5459.7 1945.49  5481.2 1946.93  5551.8 1950.08
#Mann=5,-1,0
  4189.6    0.05       0  4378.2    0.12       0  4486.0    0.05       0
  4995.3    0.03       0  4999.8    0.05       0
Bank Sta=4995.3,4999.8
Exp/Cntr=0.3,0.1

Type RM Length L Ch R = 1,66603,420,420,420
BEGIN DESCRIPTION:
South Prong Long Creek 125.0
END DESCRIPTION:
XS GIS Cut Line= 3
      1663955.00      6887788.04      1663905.00      6888588.00
      1664154.99      6888987.98
#Sta/Elev= 30
  4204.2 1950.64  4224.2 1949.28  4281.8 1947.15  4468.9 1942.27  4665.1 1937.68
  4695.1 1937.51  4745.2 1936.36  4885.5 1934.32  4928.1 1932.77  4935.6 1931.99
  4965.6 1930.30  4973.4 1929.10  4973.7 1928.60  4977.6 1928.60  4977.9 1929.10
  5008.7 1929.68  5013.4 1930.57  5028.7 1931.18  5034.6 1932.27  5217.4 1932.75
  5244.5 1933.41  5259.8 1933.25  5338.9 1935.08  5375.4 1936.63  5406.1 1939.35
  5412.0 1939.47  5427.3 1942.22  5433.2 1942.47  5448.5 1944.17  5477.4 1945.33
#Mann=4,-1,0
  4204.2    0.12       0  4468.9    0.05       0  4973.4    0.03       0
  4977.9    0.05       0
Bank Sta=4973.4,4977.9
Exp/Cntr=0.3,0.1

Type RM Length L Ch R = 1,66183,370,370,370
BEGIN DESCRIPTION:
South Prong Long Creek 124.0
END DESCRIPTION:
XS GIS Cut Line= 3
      1662755.02      6887988.02      1663555.00      6888788.00
      1663805.03      6889088.03
#Sta/Elev= 30
  3869.1 1952.62  3925.6 1951.06  3968.1 1948.33  4109.5 1943.34  4137.8 1942.71
  4151.9 1941.83  4364.0 1936.13  4745.9 1931.32  4830.7 1929.62  4929.7 1930.06
  4943.9 1929.59  4958.0 1926.24  4969.9 1925.39  4970.2 1924.89  4974.2 1924.89
  4974.5 1925.39  4986.3 1926.83  4996.9 1927.34  5021.9 1926.69  5042.7 1928.13
  5071.4 1928.23  5085.7 1929.45  5106.5 1930.49  5227.6 1931.28  5277.1 1934.05
  5291.4 1935.19  5320.0 1938.29  5369.5 1941.28  5387.7 1943.02  5391.0 1943.02
#Mann=3,-1,0
  3869.1    0.05       0  4969.9    0.05       0  4974.5    0.05       0
Bank Sta=4969.9,4974.5
Exp/Cntr=0.3,0.1

Type RM Length L Ch R = 1,65813,382,382,382
BEGIN DESCRIPTION:
Mapping XS 4b094233
END DESCRIPTION:
XS GIS Cut Line= 3
      1663130.86      6888527.68      1663288.22      6888727.00
      1663183.46      6889243.84
#Sta/Elev= 30
  4516.9 1932.58  4542.1 1932.65  4562.9 1931.94  4569.3 1932.33  4577.4 1931.95
  4612.6 1931.86  4655.9 1930.09  4662.3 1930.52  4676.7 1929.80  4705.6 1929.17
  4726.4 1929.17  4740.9 1928.43  4768.3 1928.08  4873.9 1928.26  4904.5 1927.99
  4924.9 1927.04  4967.0 1927.07  4986.1 1925.89  4996.3 1924.85  5004.2 1923.51
  5004.5 1923.01  5008.6 1923.01  5009.0 1923.51  5017.7 1923.57  5037.2 1927.20
  5047.4 1927.43  5063.3 1927.68  5159.5 1927.30  5271.8 1928.63  5298.2 1929.31
#Mann=3,-1,0
  4516.9    0.05       0  5004.2    0.05       0  5009.0    0.05       0
Bank Sta=5004.2,5009
Exp/Cntr=0.3,0.1

Type RM Length L Ch R = 1,65431,289,289,289
BEGIN DESCRIPTION:
Mapping XS 39589058
END DESCRIPTION:
XS GIS Cut Line= 2
      1662858.05      6888576.60      1663186.75      6889213.02
#Sta/Elev= 30
  4734.6 1932.96  4779.0 1931.25  4784.6 1931.67  4792.5 1931.64  4801.2 1930.95
  4823.3 1930.53  4845.5 1929.63  4860.0 1929.33  4882.5 1929.60  4895.4 1928.77
  4927.5 1927.44  4934.1 1926.84  4947.5 1926.14  4956.2 1925.37  4981.5 1924.06
  4981.9 1923.56  4986.0 1923.56  4986.4 1924.06  5028.8 1925.10  5073.8 1925.44
  5089.1 1925.80  5127.8 1925.73  5186.4 1926.27  5282.8 1926.02  5343.7 1926.67
  5371.5 1927.20  5377.7 1927.54  5415.8 1927.97  5432.3 1928.52  5450.9 1928.57
#Mann=4,-1,0
  4734.6    0.12       0  4947.5    0.05       0  4981.5    0.05       0
  4986.4    0.05       0
Bank Sta=4981.5,4986.4
Exp/Cntr=0.3,0.1

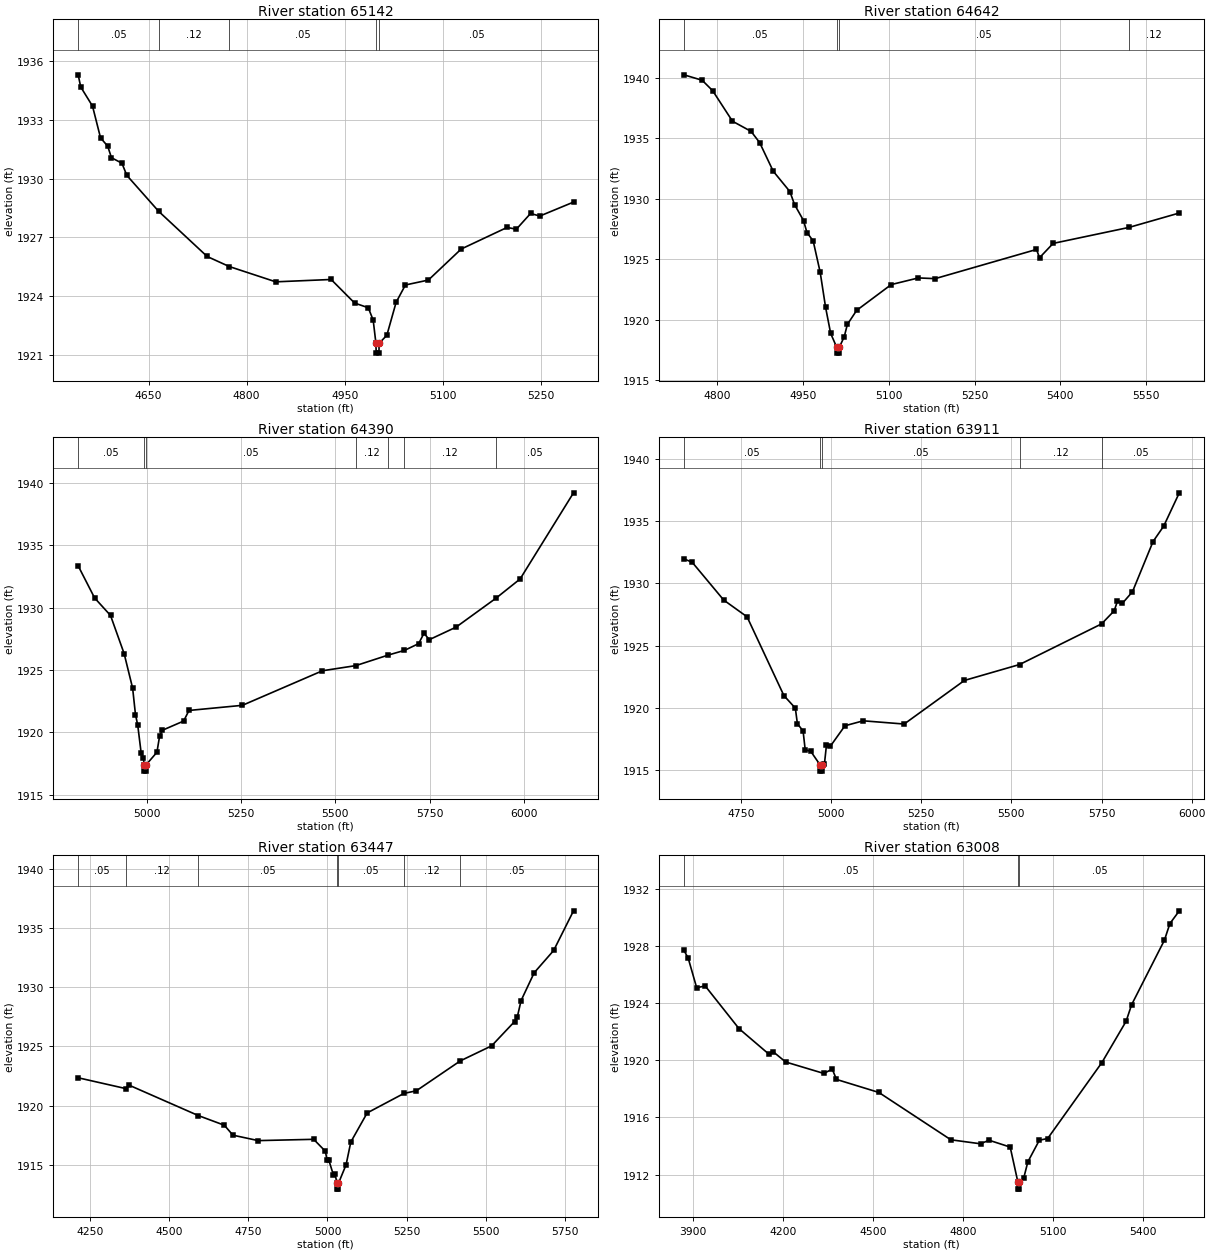
Type RM Length L Ch R = 1,65142,500,500,500
BEGIN DESCRIPTION:
Mapping XS 6275c445
END DESCRIPTION:
XS GIS Cut Line= 3
      1662679.70      6888646.58      1662802.10      6888929.84
      1663101.71      6889264.29
#Sta/Elev= 30
  4542.3 1935.28  4546.2 1934.66  4564.2 1933.69  4576.5 1932.07  4587.4 1931.65
  4593.2 1931.06  4609.2 1930.78  4616.7 1930.16  4665.4 1928.33  4739.6 1926.03
  4773.3 1925.52  4844.5 1924.74  4929.2 1924.86  4965.1 1923.66  4986.0 1923.42
  4993.5 1922.79  4997.7 1921.61  4998.1 1921.11  5002.3 1921.11  5002.6 1921.61
  5014.4 1922.02  5028.6 1923.70  5042.8 1924.58  5077.9 1924.83  5128.1 1926.41
  5198.3 1927.51  5212.5 1927.42  5234.2 1928.22  5248.4 1928.09  5299.9 1928.80
#Mann=5,-1,0
  4542.3    0.05       0  4665.4    0.12       0  4773.3    0.05       0
  4997.7    0.05       0  5002.6    0.05       0
Bank Sta=4997.7,5002.6
Exp/Cntr=0.3,0.1

Type RM Length L Ch R = 1,64642,252,252,252
BEGIN DESCRIPTION:
Mapping XS a9cb88de
END DESCRIPTION:
XS GIS Cut Line= 2
      1662266.99      6889052.24      1663064.39      6889387.99
#Sta/Elev= 30
  4742.5 1940.24  4774.3 1939.79  4792.6 1938.93  4827.2 1936.41  4859.7 1935.57
  4874.6 1934.65  4898.4 1932.28  4927.5 1930.60  4935.6 1929.53  4951.3 1928.21
  4957.3 1927.22  4968.2 1926.52  4980.4 1923.94  4989.9 1921.03  4998.7 1918.89
  5009.1 1917.76  5009.5 1917.26  5013.7 1917.26  5014.0 1917.76  5022.4 1918.61
  5027.9 1919.63  5044.1 1920.79  5104.5 1922.92  5152.0 1923.47  5181.2 1923.41
  5358.2 1925.82  5363.6 1925.14  5387.3 1926.32  5519.8 1927.64  5607.7 1928.83
#Mann=4,-1,0
  4742.5    0.05       0  5009.1    0.03       0  5014.0    0.05       0
  5519.8    0.12       0
Bank Sta=5009.1,5014
Exp/Cntr=0.3,0.1

Type RM Length L Ch R = 1,64390,479,479,479
BEGIN DESCRIPTION:
South Prong Long Creek 120.0
END DESCRIPTION:
XS GIS Cut Line= 3
      1662305.03      6889288.02      1662455.00      6889388.00
      1663254.99      6890187.99
#Sta/Elev= 30
  4819.0 1933.34  4862.5 1930.77  4904.6 1929.37  4940.7 1926.31  4963.2 1923.54
  4970.7 1921.43  4976.7 1920.58  4985.7 1918.36  4991.7 1917.96  4993.8 1917.40
  4994.1 1916.90  4998.3 1916.90  4998.7 1917.40  5027.5 1918.41  5034.6 1919.71
  5041.7 1920.17  5098.2 1920.91  5112.4 1921.76  5253.8 1922.17  5465.9 1924.94
  5554.1 1925.35  5640.4 1926.20  5682.9 1926.57  5720.5 1927.11  5734.6 1927.94
  5748.8 1927.43  5819.5 1928.43  5924.9 1930.74  5989.2 1932.29  6130.6 1939.19
#Mann=7,-1,0
  4819.0    0.05       0  4993.8    0.03       0  4998.7    0.05       0
  5554.1    0.12       0  5640.4    0.05       0  5682.9    0.12       0
  5924.9    0.05       0
Bank Sta=4993.8,4998.7
Exp/Cntr=0.3,0.1

Type RM Length L Ch R = 1,63911,464,464,464
BEGIN DESCRIPTION:
South Prong Long Creek 119.0
END DESCRIPTION:
XS GIS Cut Line= 3
      1662104.98      6889437.97      1662305.00      6889788.00
      1663105.02      6890338.01
#Sta/Elev= 30
  4591.8 1931.98  4614.9 1931.69  4702.0 1928.66  4766.8 1927.31  4869.0 1920.97
  4900.7 1919.96  4906.4 1918.71  4922.2 1918.12  4928.0 1916.62  4943.8 1916.47
  4969.4 1915.39  4969.8 1914.89  4974.0 1914.89  4974.4 1915.39  4981.3 1915.44
  4987.0 1916.98  4998.0 1916.90  5038.3 1918.54  5089.0 1918.94  5202.6 1918.68
  5369.8 1922.19  5522.7 1923.47  5750.1 1926.74  5785.1 1927.79  5794.0 1928.55
  5808.0 1928.40  5835.9 1929.33  5893.0 1933.37  5922.5 1934.61  5965.8 1937.29
#Mann=5,-1,0
  4591.8    0.05       0  4969.4    0.03       0  4974.4    0.05       0
  5522.7    0.12       0  5750.1    0.05       0
Bank Sta=4969.4,4974.4
Exp/Cntr=0.3,0.1

Type RM Length L Ch R = 1,63447,439,439,439
BEGIN DESCRIPTION:
South Prong Long Creek 118.0
END DESCRIPTION:
XS GIS Cut Line= 3
      1661627.11      6889784.45      1662305.00      6890188.00
      1663054.97      6890387.99
#Sta/Elev= 30
  4212.3 1922.35  4362.3 1921.44  4372.8 1921.73  4591.6 1919.16  4674.1 1918.34
  4701.3 1917.50  4781.2 1917.04  4956.4 1917.15  4993.4 1916.14  4998.3 1915.43
  5003.8 1915.43  5018.7 1914.14  5023.9 1914.25  5029.8 1913.44  5030.2 1912.94
  5034.4 1912.94  5034.8 1913.44  5058.8 1915.00  5073.7 1916.92  5125.4 1919.38
  5241.7 1921.03  5280.7 1921.25  5419.8 1923.78  5518.7 1925.05  5591.1 1927.10
  5599.5 1927.46  5611.8 1928.88  5653.2 1931.23  5714.7 1933.11  5777.4 1936.46
#Mann=7,-1,0
  4212.3    0.05       0  4362.3    0.12       0  4591.6    0.05       0
  5029.8    0.03       0  5034.8    0.05       0  5241.7    0.12       0
  5419.8    0.05       0
Bank Sta=5029.8,5034.8
Exp/Cntr=0.3,0.1

Type RM Length L Ch R = 1,63008,417,417,417
BEGIN DESCRIPTION:
South Prong Long Creek 117.0
END DESCRIPTION:
XS GIS Cut Line= 3
      1661255.02      6889688.02      1662055.00      6890488.00
      1662205.01      6890988.04
#Sta/Elev= 30
  3869.1 1927.67  3883.2 1927.13  3911.5 1925.06  3939.8 1925.19  4052.9 1922.20
  4151.9 1920.43  4166.1 1920.60  4208.5 1919.87  4335.8 1919.07  4364.0 1919.37
  4378.2 1918.65  4519.6 1917.74  4760.0 1914.43  4859.0 1914.15  4887.3 1914.40
  4958.0 1913.92  4983.6 1911.48  4984.0 1910.98  4988.5 1910.98  4989.0 1911.48
  5003.1 1911.75  5017.0 1912.89  5055.3 1914.40  5083.1 1914.52  5264.1 1919.83
  5345.0 1922.72  5363.2 1923.87  5472.9 1928.39  5491.1 1929.55  5522.5 1930.44
#Mann=3,-1,0
  3869.1    0.05       0  4983.6    0.03       0  4989.0    0.05       0
Bank Sta=4983.6,4989
Exp/Cntr=0.3,0.1

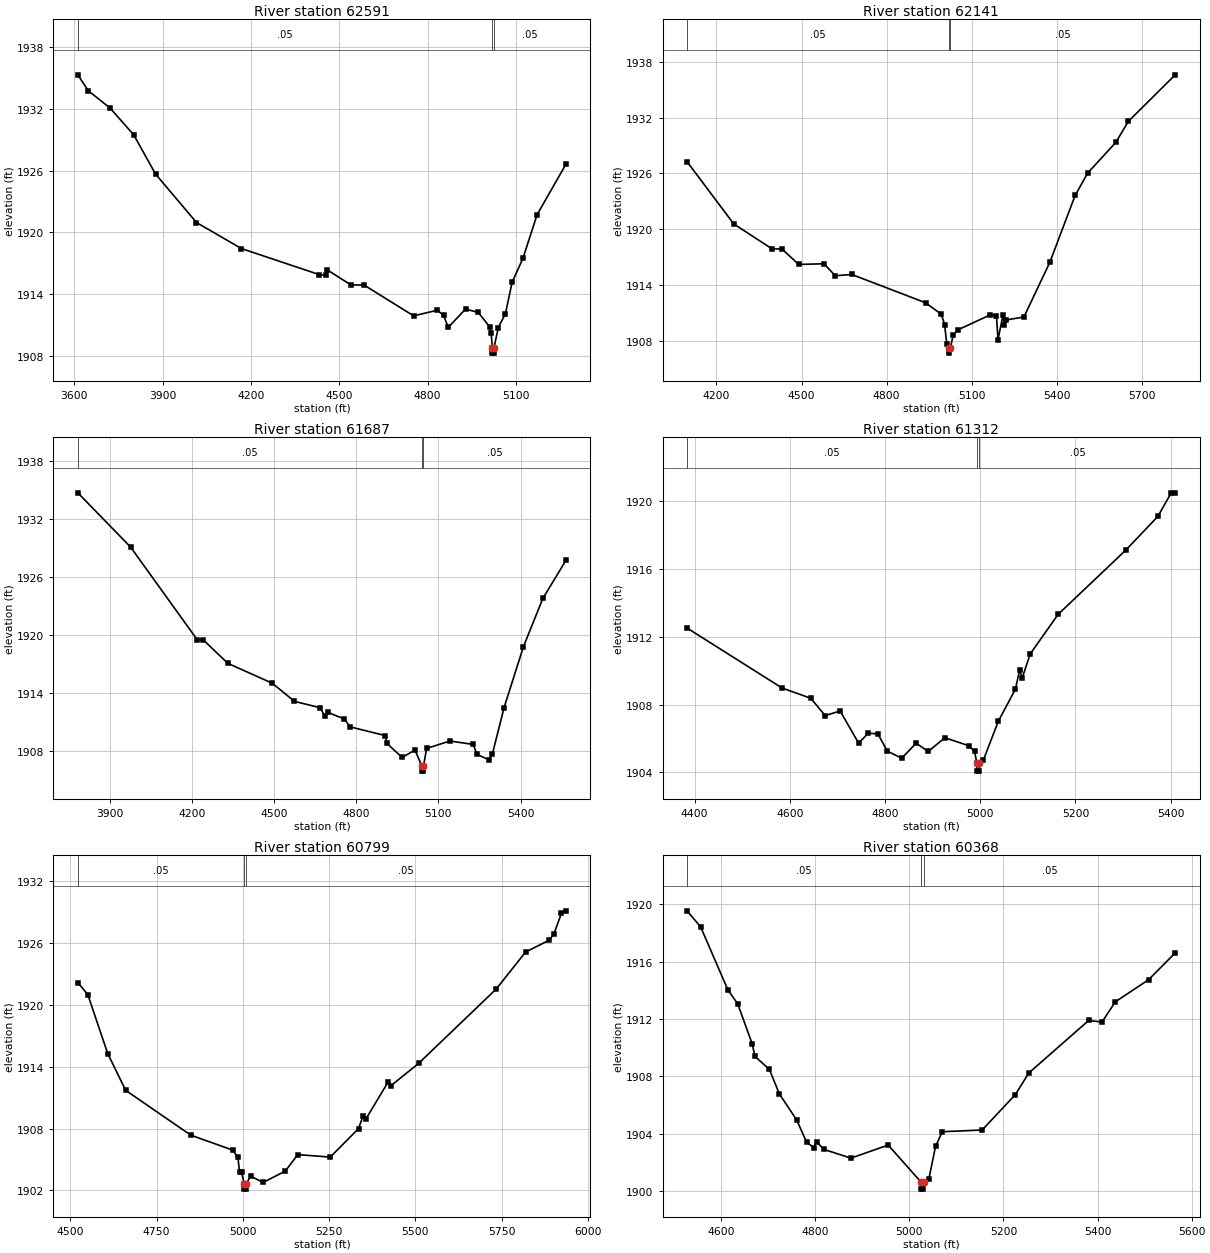
Type RM Length L Ch R = 1,62591,450,450,450
BEGIN DESCRIPTION:
South Prong Long Creek 116.0
END DESCRIPTION:
XS GIS Cut Line= 3
      1661054.99      6889537.98      1661755.00      6890738.00
      1661854.99      6890987.98
#Sta/Elev= 30
  3611.7 1935.30  3646.9 1933.76  3721.3 1932.07  3801.5 1929.47  3875.9 1925.65
  4014.8 1920.95  4167.4 1918.42  4431.6 1915.89  4453.1 1915.84  4458.9 1916.35
  4539.1 1914.89  4584.2 1914.87  4752.5 1911.88  4832.7 1912.43  4854.2 1911.93
  4869.9 1910.76  4928.6 1912.54  4971.6 1912.22  5010.4 1910.83  5015.8 1910.17
  5019.8 1908.76  5020.2 1908.26  5024.8 1908.26  5025.2 1908.76  5040.0 1910.75
  5064.2 1912.09  5087.1 1915.16  5123.5 1917.46  5171.9 1921.72  5270.2 1926.64
#Mann=3,-1,0
  3611.7    0.05       0  5019.8    0.05       0  5025.2    0.05       0
Bank Sta=5019.8,5025.2
Exp/Cntr=0.3,0.1

Type RM Length L Ch R = 1,62141,454,454,454
BEGIN DESCRIPTION:
South Prong Long Creek 115.0
END DESCRIPTION:
XS GIS Cut Line= 3
      1661054.99      6889787.99      1661455.00      6890588.00
      1661805.00      6891338.01
#Sta/Elev= 30
  4096.0 1927.28  4260.9 1920.59  4395.1 1917.93  4431.4 1917.88  4490.1 1916.24
  4579.6 1916.31  4618.7 1915.03  4677.4 1915.16  4937.3 1912.13  4993.2 1910.89
  5004.6 1909.79  5012.5 1907.69  5019.2 1907.22  5019.7 1906.72  5024.7 1907.22
  5034.6 1908.63  5050.3 1909.20  5164.6 1910.81  5187.5 1910.75  5193.0 1908.18
  5210.4 1910.76  5215.9 1909.70  5222.2 1910.28  5284.5 1910.60  5375.9 1916.47
  5465.0 1923.64  5509.1 1926.04  5608.4 1929.33  5652.6 1931.59  5818.1 1936.59
#Mann=3,-1,0
  4096.0    0.05       0  5019.2    0.03       0  5024.7    0.05       0
Bank Sta=5019.2,5024.7
Exp/Cntr=0.3,0.1

Type RM Length L Ch R = 1,61687,375,375,375
BEGIN DESCRIPTION:
South Prong Long Creek 114.0
END DESCRIPTION:
XS GIS Cut Line= 3
      1660955.00      6889588.00      1661155.00      6890788.00
      1661554.97      6891187.97
#Sta/Elev= 30
  3784.1 1934.75  3976.7 1929.13  4220.0 1919.52  4242.8 1919.49  4331.6 1917.08
  4493.8 1915.02  4574.9 1913.14  4668.6 1912.48  4686.4 1911.58  4696.5 1912.00
  4757.3 1911.31  4777.6 1910.50  4906.9 1909.59  4912.0 1908.79  4967.7 1907.33
  5014.8 1908.09  5040.3 1906.41  5040.8 1905.91  5045.4 1905.91  5045.8 1906.41
  5057.2 1908.26  5142.1 1909.03  5226.9 1908.68  5241.1 1907.65  5283.5 1907.10
  5297.6 1907.72  5340.1 1912.50  5410.8 1918.82  5481.5 1923.80  5566.3 1927.78
#Mann=3,-1,0
  3784.1    0.05       0  5040.3    0.05       0  5045.8    0.05       0
Bank Sta=5040.3,5045.8
Exp/Cntr=0.3,0.1

Type RM Length L Ch R = 1,61312,513,513,513
BEGIN DESCRIPTION:
South Prong Long Creek 113.0
END DESCRIPTION:
XS GIS Cut Line= 3
      1660856.30      6890409.48      1660921.55      6891021.81
      1661105.01      6891388.03
#Sta/Elev= 30
  4384.2 1912.52  4583.8 1908.98  4644.2 1908.37  4674.4 1907.35  4705.9 1907.62
  4744.7 1905.72  4764.9 1906.31  4785.0 1906.27  4805.1 1905.25  4835.3 1904.83
  4865.4 1905.72  4890.8 1905.23  4925.8 1906.04  4976.1 1905.57  4988.2 1905.24
  4992.8 1904.57  4993.2 1904.07  4997.9 1904.07  4998.4 1904.57  5006.9 1904.74
  5038.0 1907.01  5074.0 1908.91  5082.7 1910.03  5088.3 1909.58  5105.1 1910.99
  5163.5 1913.32  5306.2 1917.13  5373.2 1919.11  5401.2 1920.50  5409.6 1920.47
#Mann=3,-1,0
  4384.2    0.05       0  4992.8    0.03       0  4998.4    0.05       0
Bank Sta=4992.8,4998.4
Exp/Cntr=0.3,0.1

Type RM Length L Ch R = 1,60799,431,431,431
BEGIN DESCRIPTION:
South Prong Long Creek 112.0
END DESCRIPTION:
XS GIS Cut Line= 3
      1660354.99      6890487.99      1660605.00      6890888.00
      1661105.00      6891687.99
#Sta/Elev= 30
  4521.7 1922.17  4550.6 1921.00  4608.4 1915.27  4660.3 1911.71  4849.0 1907.36
  4970.4 1905.91  4985.7 1905.20  4990.5 1903.75  4996.4 1903.75  5004.1 1902.62
  5004.6 1902.12  5009.4 1902.12  5009.8 1902.62  5022.3 1903.38  5058.9 1902.77
  5123.1 1903.87  5159.1 1905.47  5253.4 1905.23  5335.4 1908.00  5347.8 1909.17
  5357.2 1908.96  5420.9 1912.51  5429.7 1912.17  5509.3 1914.32  5734.6 1921.55
  5819.5 1925.13  5886.7 1926.26  5901.4 1926.87  5923.2 1928.88  5936.8 1929.13
#Mann=3,-1,0
  4521.7    0.05       0  5004.1    0.05       0  5009.8    0.05       0
Bank Sta=5004.1,5009.8
Exp/Cntr=0.3,0.1

Type RM Length L Ch R = 1,60368,446,446,446
BEGIN DESCRIPTION:
South Prong Long Creek 111.0
END DESCRIPTION:
XS GIS Cut Line= 3
      1660105.01      6890738.02      1660355.00      6891138.00
      1660755.03      6891538.03
#Sta/Elev= 30
  4527.7 1919.54  4556.6 1918.43  4614.4 1914.05  4635.6 1913.05  4666.2 1910.28
  4672.1 1909.40  4702.8 1908.49  4724.0 1906.78  4760.6 1904.98  4781.8 1903.43
  4797.1 1903.04  4803.0 1903.46  4818.4 1902.92  4876.1 1902.31  4955.2 1903.22
  5024.8 1900.65  5025.3 1900.15  5030.1 1900.15  5030.5 1900.65  5041.8 1900.89
  5055.9 1903.13  5070.1 1904.15  5154.9 1904.27  5225.6 1906.74  5253.9 1908.24
  5381.2 1911.90  5409.5 1911.79  5437.8 1913.20  5508.5 1914.74  5565.1 1916.61
#Mann=3,-1,0
  4527.7    0.05       0  5024.8    0.03       0  5030.5    0.05       0
Bank Sta=5024.8,5030.5
Exp/Cntr=0.3,0.1

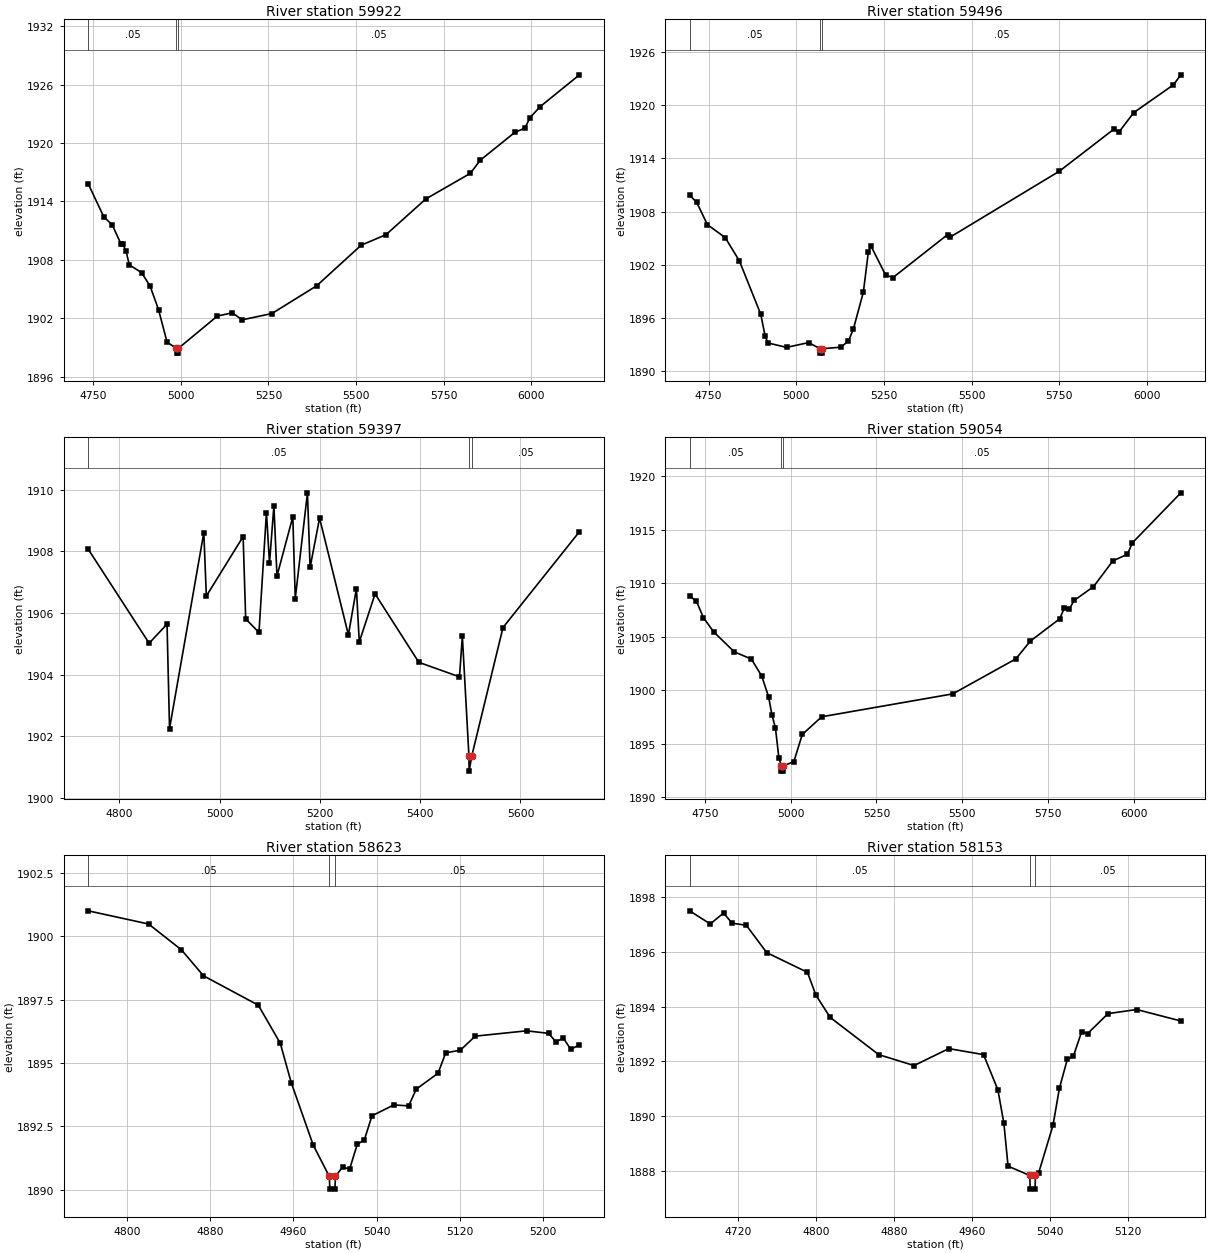
Type RM Length L Ch R = 1,59922,426,426,426
BEGIN DESCRIPTION:
South Prong Long Creek 110.0
END DESCRIPTION:
XS GIS Cut Line= 3
      1659905.01      6890938.02      1660005.00      6891188.00
      1660805.00      6891988.00
#Sta/Elev= 30
  4736.2 1915.81  4780.6 1912.42  4804.8 1911.59  4829.1 1909.67  4834.5 1909.63
  4843.9 1908.92  4853.3 1907.49  4888.3 1906.69  4912.5 1905.32  4936.8 1902.87
  4961.0 1899.54  4987.7 1898.92  4988.2 1898.42  4993.0 1898.42  4993.5 1898.92
  5104.4 1902.23  5146.9 1902.56  5175.1 1901.84  5260.0 1902.49  5387.3 1905.33
  5514.5 1909.51  5585.3 1910.59  5698.4 1914.25  5825.7 1916.89  5854.0 1918.24
  5953.0 1921.11  5981.2 1921.53  5995.4 1922.59  6023.7 1923.71  6136.8 1927.01
#Mann=3,-1,0
  4736.2    0.05       0  4987.7    0.03       0  4993.5    0.05       0
Bank Sta=4987.7,4993.5
Exp/Cntr=0.3,0.1

Type RM Length L Ch R = 1,59496,99,99,99
BEGIN DESCRIPTION:
South Prong Long Creek 109.0
END DESCRIPTION:
XS GIS Cut Line= 3
      1659655.00      6891088.00      1659705.00      6891388.00
      1660504.98      6892137.98
#Sta/Elev= 30
  4695.9 1909.84  4716.2 1909.03  4746.6 1906.52  4797.3 1905.06  4837.8 1902.43
  4898.7 1896.41  4911.3 1893.92  4918.9 1893.17  4972.2 1892.67  5035.4 1893.21
  5067.7 1892.52  5068.2 1892.02  5073.1 1892.02  5073.5 1892.52  5127.3 1892.69
  5148.8 1893.40  5162.9 1894.75  5191.3 1898.91  5205.4 1903.39  5212.3 1904.16
  5254.8 1900.83  5275.8 1900.55  5431.6 1905.40  5438.7 1905.11  5750.1 1912.55
  5905.4 1917.29  5919.6 1916.94  5962.1 1919.16  6075.4 1922.30  6096.6 1923.43
#Mann=3,-1,0
  4695.9    0.05       0  5067.7    0.05       0  5073.5    0.05       0
Bank Sta=5067.7,5073.5
Exp/Cntr=0.3,0.1

Type RM Length L Ch R = 1,59397,343,343,343
BEGIN DESCRIPTION:
Mapping XS fa05e135
END DESCRIPTION:
XS GIS Cut Line= 6
      1659639.30      6891127.40      1659622.09      6891267.94
      1659596.29      6891462.93      1659650.77      6891500.20
      1659722.45      6891528.88      1659965.71      6891963.88
#Sta/Elev= 30
  4737.8 1908.07  4859.3 1905.02  4895.0 1905.64  4900.0 1902.25  4968.4 1908.61
  4973.4 1906.55  5046.8 1908.48  5051.9 1905.81  5078.4 1905.37  5093.3 1909.26
  5099.4 1907.62  5108.2 1909.48  5114.3 1907.20  5145.9 1909.12  5150.8 1906.47
  5175.1 1909.90  5180.4 1907.48  5199.3 1909.08  5256.8 1905.29  5272.8 1906.79
  5278.5 1905.06  5310.0 1906.62  5397.3 1904.40  5478.4 1903.93  5484.1 1905.25
  5497.2 1901.37  5497.6 1900.87  5503.0 1901.37  5565.2 1905.53  5717.7 1908.64
#Mann=3,-1,0
  4737.8    0.05       0  5497.2    0.03       0  5503.0    0.05       0
Bank Sta=5497.2,5503
Exp/Cntr=0.3,0.1

Type RM Length L Ch R = 1,59054,431,431,431
BEGIN DESCRIPTION:
South Prong Long Creek 108.0
END DESCRIPTION:
XS GIS Cut Line= 3
      1659305.00      6891137.98      1659305.00      6891438.00
      1660105.00      6892238.00
#Sta/Elev= 30
  4705.6 1908.84  4725.6 1908.33  4745.6 1906.81  4775.6 1905.48  4835.6 1903.61
  4885.6 1902.93  4915.6 1901.35  4935.6 1899.42  4945.6 1897.69  4955.6 1896.51
  4965.6 1893.71  4972.7 1892.96  4973.2 1892.46  4978.1 1892.46  4978.6 1892.96
  5009.2 1893.34  5033.9 1895.89  5090.5 1897.54  5472.3 1899.68  5656.2 1902.95
  5698.6 1904.62  5783.4 1906.68  5797.6 1907.70  5811.7 1907.60  5825.9 1908.41
  5882.4 1909.70  5939.0 1912.11  5981.4 1912.73  5995.6 1913.79  6137.0 1918.47
#Mann=3,-1,0
  4705.6    0.05       0  4972.7    0.03       0  4978.6    0.05       0
Bank Sta=4972.7,4978.6
Exp/Cntr=0.3,0.1

Type RM Length L Ch R = 1,58623,470,470,470
BEGIN DESCRIPTION:
South Prong Long Creek 107.0
END DESCRIPTION:
XS GIS Cut Line= 3
      1658830.00      6891313.00      1658905.00      6891538.00
      1659065.16      6891709.60
#Sta/Elev= 30
  4762.9 1901.00  4820.9 1900.48  4852.5 1899.46  4873.6 1898.44  4926.3 1897.28
  4947.4 1895.78  4957.9 1894.23  4979.0 1891.77  4994.5 1890.53  4995.0 1890.03
  4999.9 1890.03  5000.4 1890.53  5007.2 1890.90  5014.0 1890.82  5021.3 1891.79
  5028.2 1891.98  5035.5 1892.92  5056.5 1893.35  5070.7 1893.31  5078.0 1893.97
  5099.0 1894.60  5106.3 1895.40  5120.5 1895.51  5134.7 1896.06  5184.0 1896.27
  5205.2 1896.17  5212.3 1895.83  5219.2 1895.99  5226.5 1895.54  5234.8 1895.72
#Mann=3,-1,0
  4762.9    0.05       0  4994.5    0.03       0  5000.4    0.05       0
Bank Sta=4994.5,5000.4
Exp/Cntr=0.3,0.1

Type RM Length L Ch R = 1,58153,473,473,473
BEGIN DESCRIPTION:
South Prong Long Creek 106.0
END DESCRIPTION:
XS GIS Cut Line= 3
      1658362.45      6891520.87      1658555.00      6891788.00
      1658657.29      6891928.64
#Sta/Elev= 30
  4670.6 1897.50  4691.7 1897.02  4705.4 1897.42  4714.0 1897.05  4728.7 1896.97
  4749.6 1895.97  4791.3 1895.25  4799.9 1894.42  4814.6 1893.60  4864.3 1892.24
  4900.5 1891.84  4936.1 1892.46  4971.7 1892.24  4986.4 1890.95  4992.5 1889.73
  4996.8 1888.16  5019.0 1887.82  5019.5 1887.32  5024.4 1887.32  5024.9 1887.82
  5028.1 1887.91  5042.8 1889.65  5049.4 1891.01  5057.5 1892.07  5063.7 1892.18
  5072.2 1893.08  5078.3 1893.01  5099.2 1893.74  5128.6 1893.89  5173.8 1893.47
#Mann=3,-1,0
  4670.6    0.05       0  5019.0    0.03       0  5024.9    0.05       0
Bank Sta=5019,5024.9
Exp/Cntr=0.3,0.1