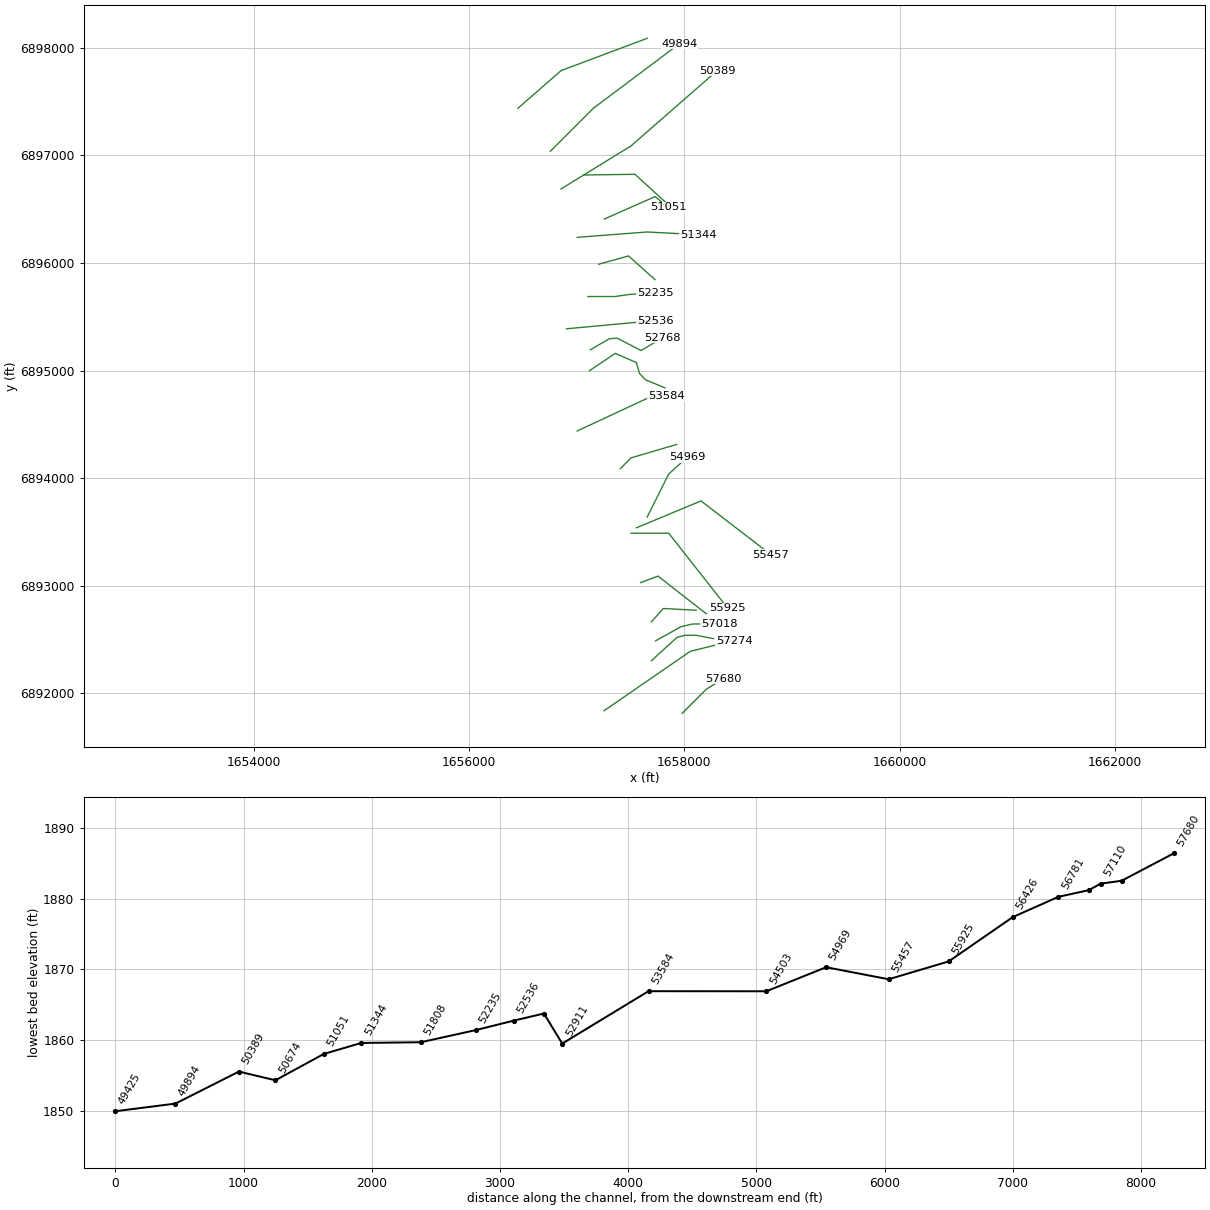
HEC-RAS study South Prong Long Creek.prj: South Prong Long Creek Base Level Engineering

--- South Prong Long Creek.g01 (geometry) --- (continued)

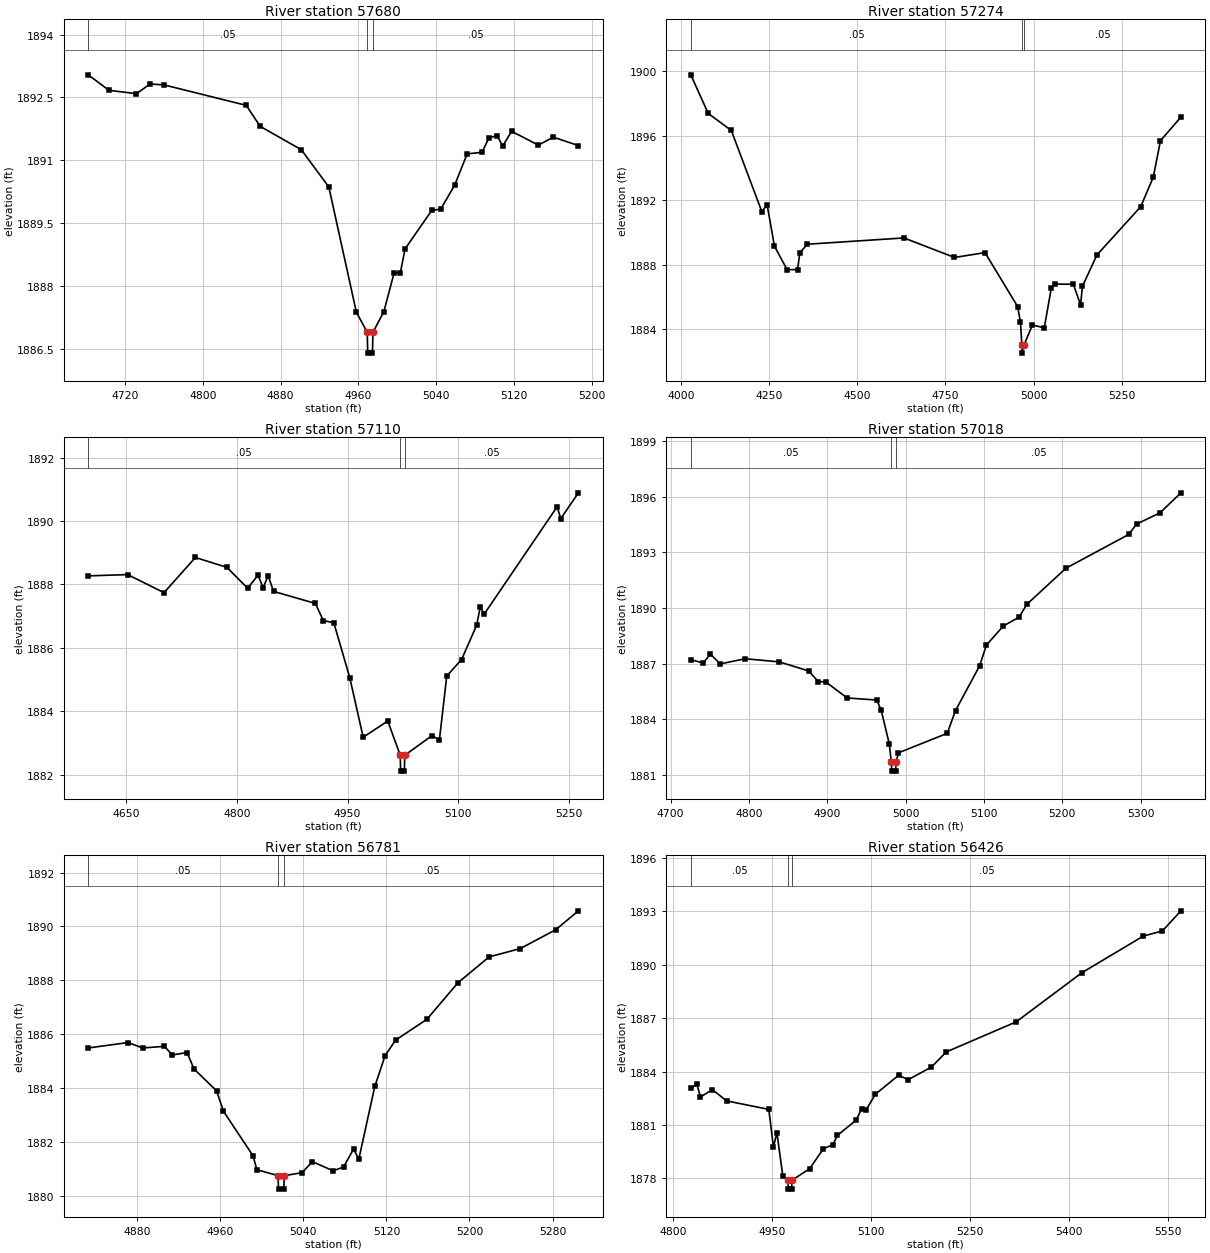
Type RM Length L Ch R = 1,57680,406,406,406
BEGIN DESCRIPTION:
South Prong Long Creek 105.0
END DESCRIPTION:
XS GIS Cut Line= 3
      1657980.00      6891813.00      1658205.00      6892038.00
      1658363.49      6892135.53
#Sta/Elev= 30
  4682.2 1893.04  4703.4 1892.67  4731.7 1892.59  4745.8 1892.82  4760.0 1892.80
  4844.8 1892.31  4859.0 1891.81  4901.4 1891.25  4929.7 1890.36  4958.0 1887.37
  4969.2 1886.89  4969.7 1886.39  4974.6 1886.39  4975.1 1886.89  4986.3 1887.38
  4996.9 1888.31  5003.3 1888.31  5008.1 1888.88  5035.6 1889.80  5044.8 1889.83
  5059.1 1890.40  5072.0 1891.15  5087.4 1891.19  5094.3 1891.53  5102.8 1891.59
  5108.6 1891.34  5117.8 1891.69  5145.3 1891.36  5160.7 1891.55  5186.5 1891.35
#Mann=3,-1,0
  4682.2    0.05       0  4969.2    0.03       0  4975.1    0.05       0
Bank Sta=4969.2,4975.1
Exp/Cntr=0.3,0.1

Type RM Length L Ch R = 1,57274,164,164,164
BEGIN DESCRIPTION:
South Prong Long Creek 104.0
END DESCRIPTION:
XS GIS Cut Line= 3
      1657255.02      6891838.01      1658055.64      6892389.72
      1658461.17      6892490.23
#Sta/Elev= 30
  4027.7 1899.77  4077.0 1897.38  4142.6 1896.32  4229.2 1891.29  4244.1 1891.72
  4265.0 1889.15  4300.9 1887.69  4330.6 1887.70  4336.7 1888.72  4357.7 1889.27
  4632.3 1889.66  4775.6 1888.45  4862.2 1888.75  4954.8 1885.40  4962.8 1884.42
  4966.7 1883.02  4967.2 1882.52  4972.6 1883.02  4996.6 1884.26  5030.3 1884.09
  5050.4 1886.58  5061.2 1886.80  5112.7 1886.79  5133.2 1885.51  5138.4 1886.66
  5179.8 1888.61  5303.9 1891.60  5339.3 1893.42  5359.9 1895.69  5417.8 1897.15
#Mann=3,-1,0
  4027.7    0.05       0  4966.7    0.03       0  4972.6    0.05       0
Bank Sta=4966.7,4972.6
Exp/Cntr=0.3,0.1

Type RM Length L Ch R = 1,57110,92,92,92
BEGIN DESCRIPTION:
Mapping XS 7a8c2a7d
END DESCRIPTION:
XS GIS Cut Line= 5
      1657694.93      6892303.01      1657931.03      6892518.28
      1658007.42      6892539.11      1658108.12      6892539.11
      1658270.67      6892507.99
#Sta/Elev= 30
  4598.2 1888.27  4651.6 1888.31  4700.9 1887.74  4743.5 1888.85  4786.1 1888.54
  4814.4 1887.88  4828.4 1888.29  4835.4 1887.90  4842.2 1888.27  4849.6 1887.78
  4906.3 1887.40  4917.0 1886.86  4931.3 1886.79  4952.9 1885.06  4971.1 1883.18
  5004.5 1883.69  5021.4 1882.61  5021.9 1882.11  5027.0 1882.11  5027.5 1882.61
  5064.5 1883.23  5074.5 1883.09  5084.5 1885.11  5104.6 1885.63  5125.0 1886.71
  5130.1 1887.30  5135.2 1887.06  5234.2 1890.45  5239.2 1890.08  5263.1 1890.89
#Mann=3,-1,0
  4598.2    0.05       0  5021.4    0.03       0  5027.5    0.05       0
Bank Sta=5021.4,5027.5
Exp/Cntr=0.3,0.1

Type RM Length L Ch R = 1,57018,237,237,237
BEGIN DESCRIPTION:
Mapping XS 0a4c0fe6
END DESCRIPTION:
XS GIS Cut Line= 4
      1657733.10      6892487.02      1657969.23      6892618.97
      1658073.39      6892643.28      1658321.71      6892646.73
#Sta/Elev= 30
  4725.7 1887.21  4741.5 1887.03  4750.8 1887.51  4763.2 1886.98  4795.2 1887.26
  4838.6 1887.09  4876.3 1886.60  4888.3 1886.03  4898.0 1886.01  4925.4 1885.14
  4963.1 1885.03  4968.8 1884.48  4979.1 1882.67  4981.7 1881.69  4982.2 1881.19
  4987.3 1881.19  4987.8 1881.69  4990.9 1882.18  5053.1 1883.23  5063.7 1884.46
  5094.5 1886.88  5103.2 1888.00  5124.8 1889.03  5144.8 1889.50  5154.8 1890.20
  5204.8 1892.15  5284.8 1893.97  5294.8 1894.53  5324.8 1895.14  5351.5 1896.22
#Mann=3,-1,0
  4725.7    0.05       0  4981.7    0.03       0  4987.8    0.05       0
Bank Sta=4981.7,4987.8
Exp/Cntr=0.3,0.1

Type RM Length L Ch R = 1,56781,355,355,355
BEGIN DESCRIPTION:
South Prong Long Creek 103.0
END DESCRIPTION:
XS GIS Cut Line= 3
      1657694.92      6892664.11      1657805.00      6892788.00
      1658110.84      6892771.79
#Sta/Elev= 30
  4832.9 1885.49  4871.1 1885.69  4885.3 1885.49  4906.2 1885.55  4913.8 1885.23
  4928.0 1885.32  4934.7 1884.71  4956.4 1883.90  4963.1 1883.14  4991.5 1881.49
  4995.3 1880.97  5015.6 1880.75  5016.1 1880.25  5021.2 1880.25  5021.7 1880.75
  5038.7 1880.86  5048.7 1881.27  5068.7 1880.93  5078.7 1881.07  5088.4 1881.74
  5093.4 1881.36  5108.8 1884.06  5118.8 1885.21  5128.8 1885.78  5158.9 1886.55
  5188.9 1887.91  5218.9 1888.87  5249.0 1889.18  5283.1 1889.88  5304.9 1890.58
#Mann=3,-1,0
  4832.9    0.05       0  5015.6    0.03       0  5021.7    0.05       0
Bank Sta=5015.6,5021.7
Exp/Cntr=0.3,0.1

Type RM Length L Ch R = 1,56426,501,501,501
BEGIN DESCRIPTION:
South Prong Long Creek 102.0
END DESCRIPTION:
XS GIS Cut Line= 3
      1657594.24      6893028.70      1657756.17      6893089.02
      1658205.01      6892738.00
#Sta/Elev= 30
  4827.2 1883.06  4836.4 1883.30  4841.8 1882.57  4860.0 1882.98  4881.4 1882.35
  4945.4 1881.87  4952.4 1879.76  4957.7 1880.56  4966.7 1878.11  4974.4 1877.89
  4974.9 1877.39  4980.0 1877.39  4980.5 1877.89  5007.3 1878.54  5028.1 1879.66
  5042.6 1879.89  5049.3 1880.41  5077.9 1881.27  5086.0 1881.91  5092.3 1881.81
  5106.8 1882.72  5142.1 1883.79  5156.5 1883.54  5191.8 1884.25  5214.3 1885.10
  5320.2 1886.79  5419.7 1889.55  5512.8 1891.61  5541.8 1891.90  5569.8 1893.03
#Mann=3,-1,0
  4827.2    0.05       0  4974.4    0.03       0  4980.5    0.05       0
Bank Sta=4974.4,4980.5
Exp/Cntr=0.3,0.1

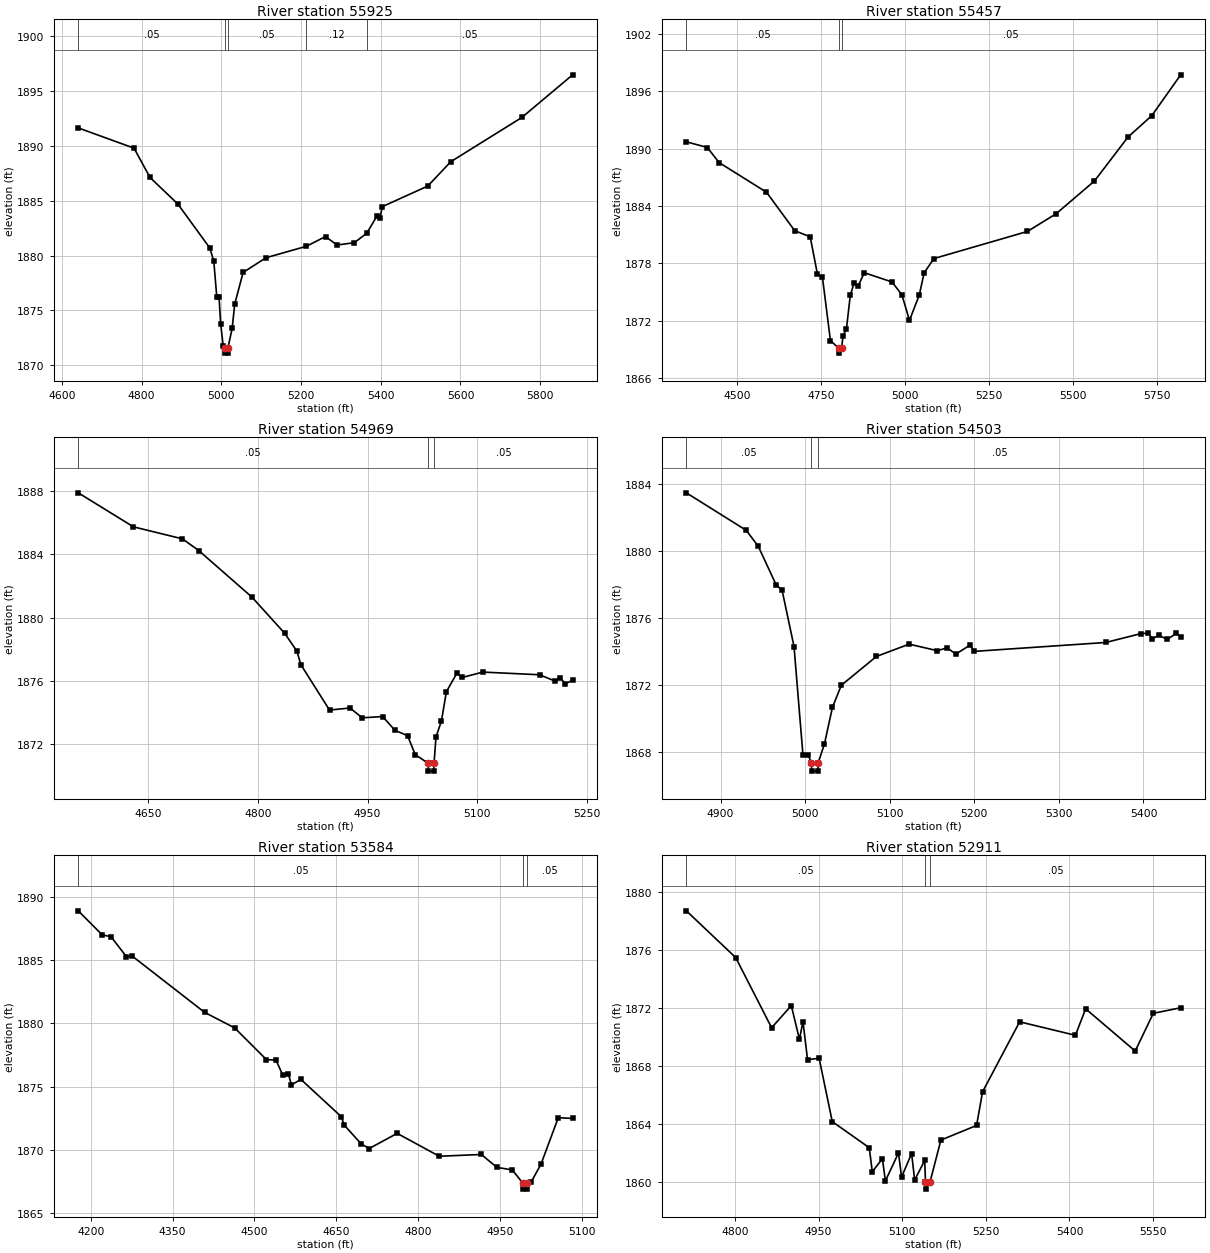
Type RM Length L Ch R = 1,55925,468,468,468
BEGIN DESCRIPTION:
South Prong Long Creek 101.0
END DESCRIPTION:
XS GIS Cut Line= 3
      1657504.99      6893488.00      1657855.00      6893488.00
      1658404.98      6892788.02
#Sta/Elev= 30
  4641.1 1891.65  4781.1 1889.80  4821.1 1887.13  4891.1 1884.70  4971.1 1880.70
  4981.1 1879.50  4988.6 1876.24  4994.3 1876.24  4998.3 1873.81  5004.7 1871.75
  5008.8 1871.61  5009.3 1871.11  5016.2 1871.11  5016.7 1871.61  5027.2 1873.36
  5033.6 1875.58  5054.7 1878.47  5112.2 1879.81  5213.1 1880.85  5261.4 1881.74
  5290.3 1880.97  5333.6 1881.18  5364.8 1882.04  5389.7 1883.57  5397.8 1883.44
  5404.1 1884.47  5518.0 1886.35  5575.8 1888.57  5753.9 1892.60  5881.3 1896.49
#Mann=5,-1,0
  4641.1    0.05       0  5008.8    0.03       0  5016.7    0.05       0
  5213.1    0.12       0  5364.8    0.05       0
Bank Sta=5008.8,5016.7
Exp/Cntr=0.3,0.1

Type RM Length L Ch R = 1,55457,488,488,488
BEGIN DESCRIPTION:
South Prong Long Creek 100.0
END DESCRIPTION:
XS GIS Cut Line= 3
      1657555.00      6893538.00      1658155.00      6893788.00
      1658805.03      6893287.97
#Sta/Elev= 30
  4349.4 1890.72  4411.7 1890.12  4446.9 1888.54  4587.7 1885.44  4671.7 1881.41
  4717.7 1880.77  4739.4 1876.83  4754.0 1876.57  4777.9 1869.90  4803.1 1869.09
  4803.6 1868.59  4811.1 1869.09  4815.2 1870.37  4825.5 1871.14  4836.9 1874.63
  4847.7 1875.89  4860.2 1875.61  4878.6 1877.01  4960.9 1876.04  4990.2 1874.71
  5013.0 1872.02  5042.0 1874.67  5056.5 1876.99  5085.5 1878.49  5363.7 1881.33
  5448.9 1883.18  5563.0 1886.61  5662.7 1891.21  5733.4 1893.45  5819.5 1897.73
#Mann=3,-1,0
  4349.4    0.05       0  4803.1    0.03       0  4811.1    0.05       0
Bank Sta=4803.1,4811.1
Exp/Cntr=0.3,0.1

Type RM Length L Ch R = 1,54969,466,466,466
BEGIN DESCRIPTION:
South Prong Long Creek 99.0
END DESCRIPTION:
XS GIS Cut Line= 3
      1657654.98      6893637.97      1657855.00      6894038.00
      1658024.79      6894191.89
#Sta/Elev= 30
  4554.1 1887.88  4629.6 1885.73  4696.7 1884.97  4719.0 1884.23  4791.7 1881.29
  4836.4 1879.01  4853.2 1877.88  4858.8 1877.01  4897.9 1874.15  4925.9 1874.28
  4942.7 1873.66  4970.6 1873.74  4987.4 1872.87  5004.7 1872.53  5015.2 1871.33
  5032.8 1870.79  5033.3 1870.29  5040.4 1870.29  5040.9 1870.79  5043.6 1872.46
  5051.0 1873.45  5057.8 1875.31  5072.0 1876.47  5079.4 1876.21  5107.8 1876.55
  5185.5 1876.38  5206.5 1875.98  5213.9 1876.18  5220.6 1875.80  5230.5 1876.05
#Mann=3,-1,0
  4554.1    0.05       0  5032.8    0.03       0  5040.9    0.05       0
Bank Sta=5032.8,5040.9
Exp/Cntr=0.3,0.1

Type RM Length L Ch R = 1,54503,919,919,919
BEGIN DESCRIPTION:
South Prong Long Creek 98.0
END DESCRIPTION:
XS GIS Cut Line= 3
      1657404.98      6894087.98      1657505.00      6894188.00
      1657930.04      6894313.01
#Sta/Elev= 30
  4859.5 1883.46  4930.2 1881.23  4944.4 1880.29  4965.6 1877.99  4972.7 1877.66
  4986.8 1874.31  4997.4 1867.84  5003.6 1867.84  5007.3 1867.39  5007.8 1866.89
  5014.9 1866.89  5015.4 1867.39  5022.8 1868.51  5032.2 1870.68  5042.7 1872.00
  5084.3 1873.72  5122.9 1874.45  5156.3 1874.06  5167.7 1874.23  5178.2 1873.86
  5194.8 1874.39  5200.0 1874.02  5355.4 1874.55  5397.1 1875.08  5405.4 1875.10
  5410.6 1874.78  5417.9 1874.97  5428.3 1874.74  5438.7 1875.09  5444.0 1874.88
#Mann=3,-1,0
  4859.5    0.05       0  5007.3    0.03       0  5015.4    0.05       0
Bank Sta=5007.3,5015.4
Exp/Cntr=0.3,0.1

Type RM Length L Ch R = 1,53584,673,673,673
BEGIN DESCRIPTION:
South Prong Long Creek 97.0
END DESCRIPTION:
XS GIS Cut Line= 3
      1657005.00      6894438.00      1657755.00      6894788.00
      1657830.00      6894763.00
#Sta/Elev= 30
  4176.9 1888.91  4221.0 1887.00  4236.8 1886.87  4265.2 1885.29  4276.2 1885.32
  4408.6 1880.88  4463.8 1879.65  4522.1 1877.14  4539.5 1877.11  4552.1 1875.91
  4562.3 1876.01  4567.9 1875.14  4585.2 1875.58  4659.3 1872.63  4664.8 1871.96
  4695.6 1870.49  4710.5 1870.11  4761.8 1871.31  4839.0 1869.50  4916.3 1869.64
  4944.6 1868.62  4973.0 1868.42  4991.8 1867.40  4992.3 1866.90  4999.4 1866.90
  4999.9 1867.40  5007.2 1867.44  5025.6 1868.87  5057.3 1872.55  5083.6 1872.49
#Mann=3,-1,0
  4176.9    0.05       0  4991.8    0.03       0  4999.9    0.05       0
Bank Sta=4991.8,4999.9
Exp/Cntr=0.3,0.1

Type RM Length L Ch R = 1,52911,143,143,143
BEGIN DESCRIPTION:
Mapping XS 09ce8bbf
END DESCRIPTION:
XS GIS Cut Line= 6
      1657120.03      6894999.01      1657358.06      6895159.18
      1657553.81      6895074.65      1657583.51      6894973.72
      1657638.33      6894914.49      1657820.39      6894839.01
#Sta/Elev= 30
  4713.0 1878.72  4801.5 1875.49  4865.9 1870.64  4901.2 1872.17  4915.8 1869.84
  4922.1 1871.07  4930.3 1868.44  4951.1 1868.53  4974.6 1864.16  5041.0 1862.35
  5046.4 1860.69  5064.5 1861.59  5069.9 1860.06  5093.4 1861.99  5098.9 1860.32
  5116.9 1861.95  5122.4 1860.12  5140.4 1861.47  5141.8 1859.99  5142.3 1859.49
  5150.0 1859.99  5169.4 1862.88  5233.4 1863.89  5244.2 1866.22  5310.6 1871.05
  5410.6 1870.12  5429.0 1871.95  5517.8 1869.03  5550.3 1871.64  5599.4 1872.02
#Mann=3,-1,0
  4713.0    0.05       0  5141.8    0.03       0  5150.0    0.05       0
Bank Sta=5141.8,5150
Exp/Cntr=0.3,0.1

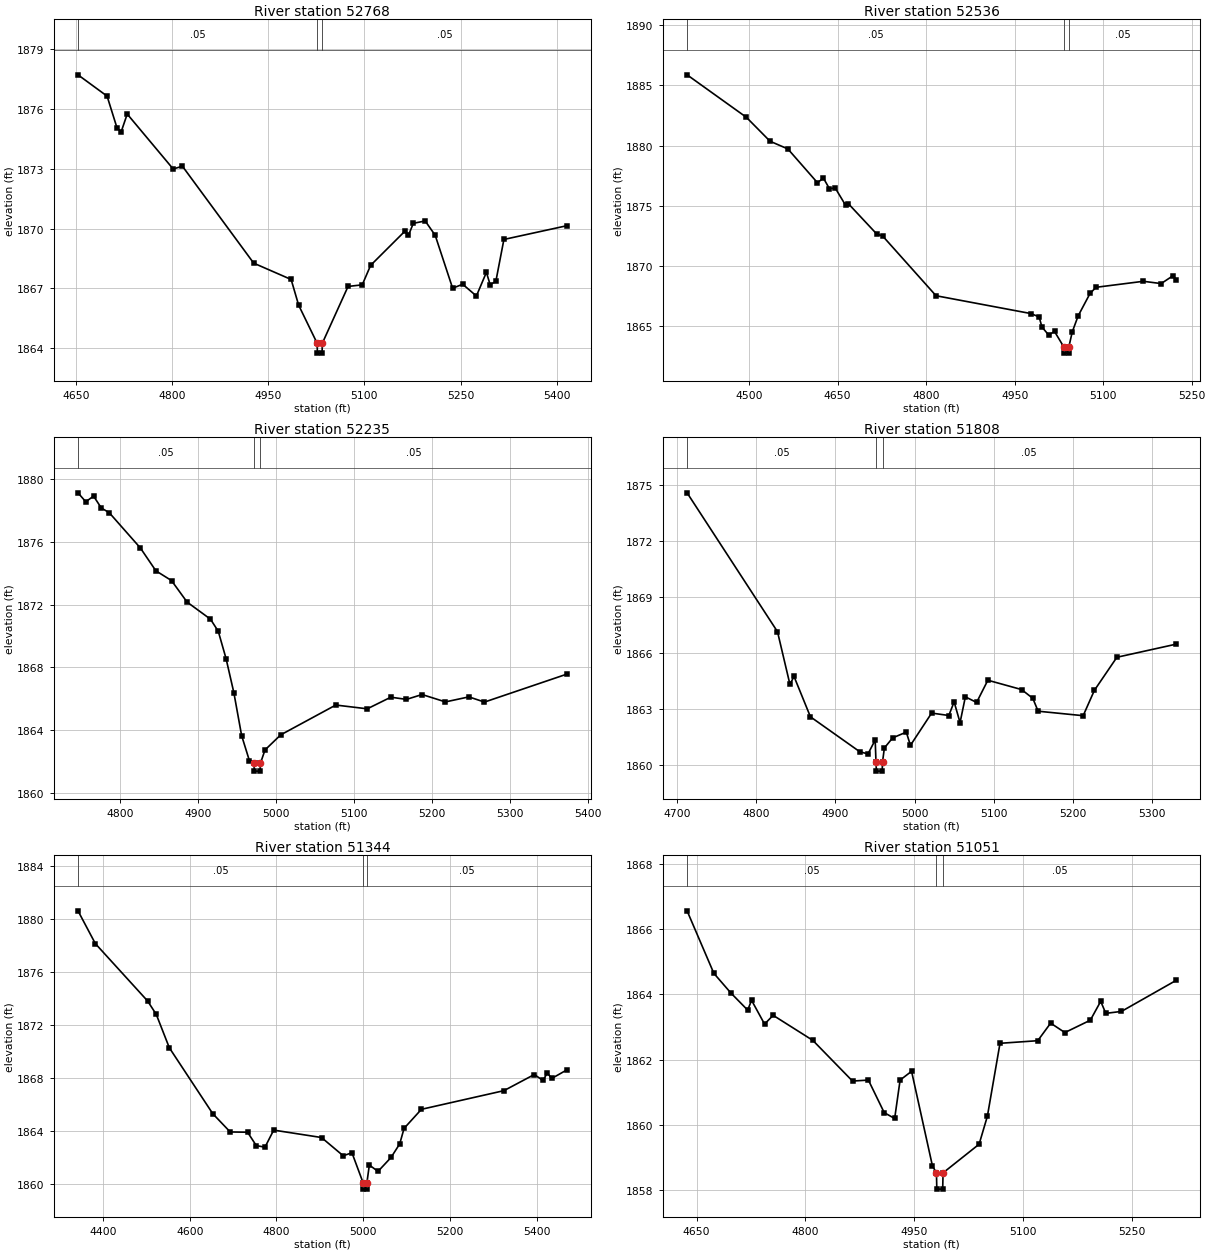
Type RM Length L Ch R = 1,52768,232,232,232
BEGIN DESCRIPTION:
Mapping XS cc13dbf5
END DESCRIPTION:
XS GIS Cut Line= 5
      1657126.70      6895192.53      1657302.45      6895294.86
      1657375.86      6895301.54      1657598.30      6895185.87
      1657800.28      6895305.60
#Sta/Elev= 30
  4653.2 1877.72  4698.6 1876.65  4714.3 1875.03  4720.7 1874.87  4730.0 1875.75
  4801.7 1872.99  4816.1 1873.13  4927.3 1868.26  4985.7 1867.44  4997.4 1866.15
  5026.2 1864.24  5026.7 1863.74  5033.9 1863.74  5034.4 1864.24  5074.5 1867.09
  5096.6 1867.17  5109.7 1868.15  5163.0 1869.86  5168.6 1869.65  5176.3 1870.26
  5194.8 1870.38  5210.4 1869.66  5237.6 1867.00  5253.3 1867.20  5274.7 1866.61
  5290.3 1867.80  5296.1 1867.18  5305.0 1867.34  5317.6 1869.45  5415.8 1870.14
#Mann=3,-1,0
  4653.2    0.05       0  5026.2    0.03       0  5034.4    0.05       0
Bank Sta=5026.2,5034.4
Exp/Cntr=0.3,0.1

Type RM Length L Ch R = 1,52536,301,301,301
BEGIN DESCRIPTION:
South Prong Long Creek 96.0
END DESCRIPTION:
XS GIS Cut Line= 3
      1656904.95      6895388.00      1657507.56      6895443.89
      1657730.05      6895463.00
#Sta/Elev= 30
  4394.8 1885.88  4495.3 1882.35  4535.4 1880.36  4565.6 1879.72  4615.8 1876.91
  4625.8 1877.30  4635.9 1876.43  4645.9 1876.47  4663.3 1875.05  4668.3 1875.16
  4716.2 1872.65  4726.3 1872.48  4816.7 1867.52  4977.3 1866.04  4991.4 1865.76
  4996.2 1864.92  5007.5 1864.26  5017.5 1864.55  5033.4 1863.25  5033.9 1862.75
  5041.2 1862.75  5041.7 1863.25  5047.6 1864.52  5057.6 1865.85  5077.7 1867.71
  5087.8 1868.22  5168.1 1868.72  5198.2 1868.53  5218.2 1869.18  5223.3 1868.85
#Mann=3,-1,0
  4394.8    0.05       0  5033.4    0.03       0  5041.7    0.05       0
Bank Sta=5033.4,5041.7
Exp/Cntr=0.3,0.1

Type RM Length L Ch R = 1,52235,427,427,427
BEGIN DESCRIPTION:
South Prong Long Creek 95.0
END DESCRIPTION:
XS GIS Cut Line= 4
      1657105.02      6895688.00      1657355.00      6895688.00
      1657497.17      6895708.31      1657730.58      6895720.22
#Sta/Elev= 30
  4745.8 1879.12  4755.8 1878.55  4765.8 1878.91  4775.8 1878.15  4785.8 1877.86
  4825.8 1875.61  4845.8 1874.15  4865.8 1873.53  4885.8 1872.16  4915.8 1871.07
  4925.8 1870.30  4935.8 1868.56  4945.8 1866.39  4955.8 1863.65  4965.8 1862.05
  4971.6 1861.89  4972.1 1861.39  4979.4 1861.39  4979.9 1861.89  4985.8 1862.74
  5005.9 1863.70  5076.6 1865.60  5117.0 1865.36  5147.2 1866.10  5167.3 1865.96
  5187.3 1866.27  5217.3 1865.80  5247.4 1866.12  5267.4 1865.79  5373.1 1867.57
#Mann=3,-1,0
  4745.8    0.05       0  4971.6    0.03       0  4979.9    0.05       0
Bank Sta=4971.6,4979.9
Exp/Cntr=0.3,0.1

Type RM Length L Ch R = 1,51808,464,464,464
BEGIN DESCRIPTION:
South Prong Long Creek 94.0
END DESCRIPTION:
XS GIS Cut Line= 3
      1657204.97      6895987.99      1657481.66      6896065.34
      1657727.67      6895845.08
#Sta/Elev= 30
  4712.7 1874.59  4826.9 1867.15  4842.6 1864.33  4847.8 1864.75  4868.5 1862.59
  4930.8 1860.72  4941.2 1860.60  4950.3 1861.35  4951.3 1860.18  4951.8 1859.68
  4959.1 1859.68  4959.6 1860.18  4961.9 1860.92  4972.3 1861.46  4989.6 1861.77
  4994.8 1861.06  5021.6 1862.79  5043.3 1862.66  5050.0 1863.39  5057.5 1862.28
  5064.2 1863.66  5078.4 1863.36  5092.6 1864.55  5135.2 1864.05  5149.4 1863.58
  5156.1 1862.89  5213.0 1862.65  5227.2 1864.01  5255.6 1865.78  5330.2 1866.48
#Mann=3,-1,0
  4712.7    0.05       0  4951.3    0.03       0  4959.6    0.05       0
Bank Sta=4951.3,4959.6
Exp/Cntr=0.3,0.1

Type RM Length L Ch R = 1,51344,293,293,293
BEGIN DESCRIPTION:
South Prong Long Creek 93.0
END DESCRIPTION:
XS GIS Cut Line= 3
      1657004.97      6896238.00      1657655.00      6896288.00
      1658129.99      6896263.00
#Sta/Elev= 30
  4342.3 1880.61  4382.4 1878.13  4502.8 1873.80  4522.9 1872.78  4553.0 1870.26
  4653.2 1865.28  4693.4 1863.90  4733.5 1863.88  4753.5 1862.87  4773.6 1862.75
  4793.7 1864.04  4904.0 1863.48  4954.1 1862.10  4974.2 1862.33  4999.7 1860.08
  5000.2 1859.58  5008.3 1859.58  5008.8 1860.08  5014.3 1861.40  5034.3 1860.92
  5064.3 1861.97  5084.4 1863.00  5094.4 1864.17  5134.4 1865.61  5324.7 1867.02
  5394.8 1868.24  5414.8 1867.79  5424.8 1868.36  5434.9 1867.94  5469.9 1868.59
#Mann=3,-1,0
  4342.3    0.05       0  4999.7    0.03       0  5008.8    0.05       0
Bank Sta=4999.7,5008.8
Exp/Cntr=0.3,0.1

Type RM Length L Ch R = 1,51051,377,377,377
BEGIN DESCRIPTION:
Mapping XS b91e6eb2
END DESCRIPTION:
XS GIS Cut Line= 3
      1657256.56      6896407.91      1657729.05      6896617.24
      1657848.69      6896515.55
#Sta/Elev= 30
  4637.0 1866.57  4673.9 1864.65  4697.2 1864.05  4720.5 1863.52  4725.9 1863.82
  4743.8 1863.09  4755.6 1863.36  4810.3 1862.59  4865.0 1861.34  4886.9 1861.37
  4908.7 1860.37  4923.1 1860.19  4930.6 1861.37  4946.4 1861.64  4975.2 1858.73
  4980.7 1858.52  4981.2 1858.02  4989.3 1858.02  4989.8 1858.52  5039.5 1859.40
  5050.9 1860.26  5068.3 1862.50  5120.3 1862.58  5138.1 1863.12  5157.7 1862.83
  5192.8 1863.21  5207.1 1863.79  5214.1 1863.42  5235.7 1863.48  5310.8 1864.43
#Mann=3,-1,0
  4637.0    0.05       0  4980.7    0.03       0  4989.8    0.05       0
Bank Sta=4980.7,4989.8
Exp/Cntr=0.3,0.1

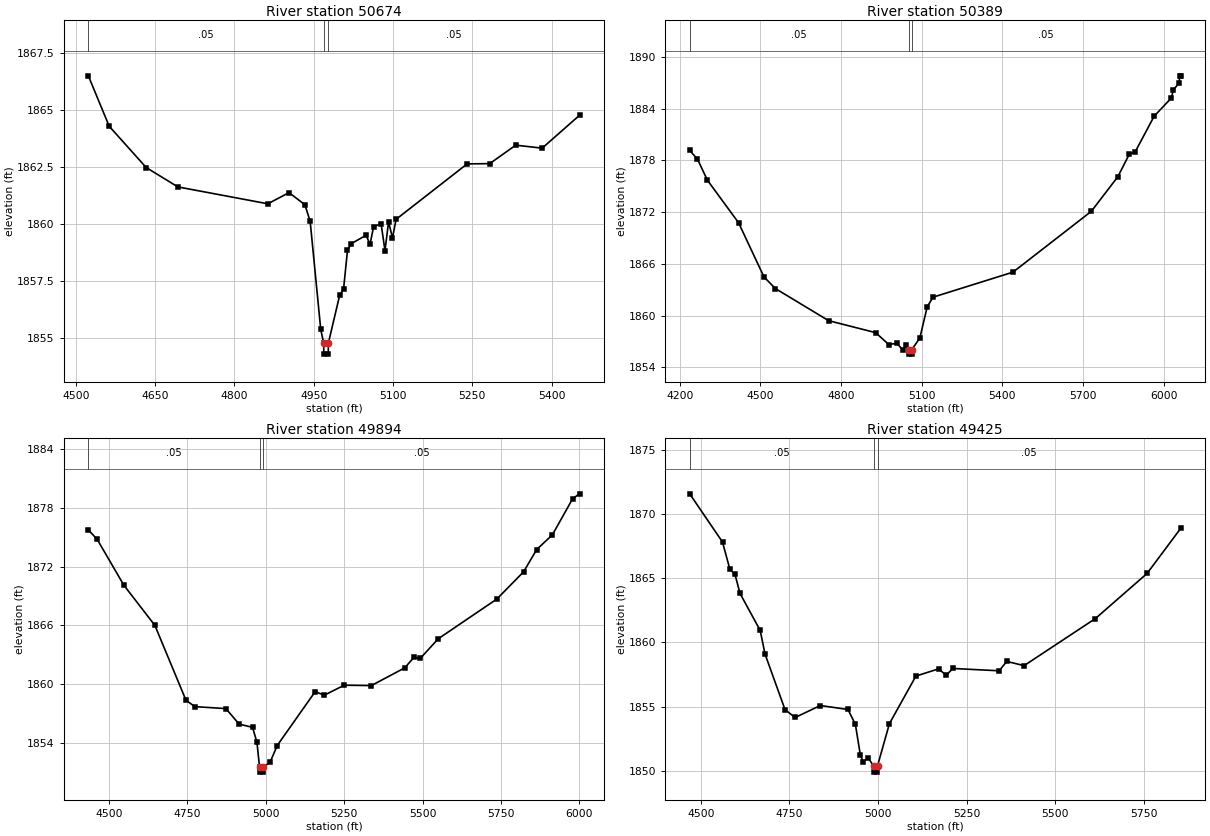
Type RM Length L Ch R = 1,50674,285,285,285
BEGIN DESCRIPTION:
South Prong Long Creek 92.0
END DESCRIPTION:
XS GIS Cut Line= 3
      1657065.58      6896817.59      1657541.63      6896824.26
      1657875.62      6896518.52
#Sta/Elev= 30
  4523.9 1866.50  4563.3 1864.29  4633.3 1862.48  4693.3 1861.63  4863.4 1860.89
  4903.4 1861.38  4933.4 1860.85  4943.4 1860.12  4963.4 1855.38  4968.8 1854.80
  4969.3 1854.30  4977.5 1854.30  4978.0 1854.80  4999.2 1856.88  5006.6 1857.16
  5014.0 1858.85  5020.8 1859.14  5049.2 1859.51  5056.6 1859.11  5063.3 1859.88
  5077.5 1860.02  5084.9 1858.84  5091.7 1860.10  5099.1 1859.39  5105.9 1860.21
  5240.3 1862.64  5282.9 1862.65  5332.2 1863.46  5382.2 1863.33  5452.8 1864.77
#Mann=3,-1,0
  4523.9    0.05       0  4968.8    0.03       0  4978.0    0.05       0
Bank Sta=4968.8,4978
Exp/Cntr=0.3,0.1

Type RM Length L Ch R = 1,50389,495,495,495
BEGIN DESCRIPTION:
South Prong Long Creek 91.0
END DESCRIPTION:
XS GIS Cut Line= 3
      1656854.97      6896687.98      1657505.00      6897088.00
      1658305.02      6897788.02
#Sta/Elev= 30
  4237.2 1879.15  4266.2 1878.15  4302.9 1875.71  4418.9 1870.77  4513.5 1864.48
  4556.1 1863.13  4753.9 1859.41  4928.9 1858.02  4977.3 1856.64  5007.6 1856.79
  5028.5 1856.05  5042.7 1856.54  5051.2 1856.03  5051.7 1855.53  5062.1 1855.53
  5062.6 1856.03  5093.0 1857.40  5120.5 1861.04  5142.4 1862.14  5439.4 1865.04
  5730.8 1872.10  5829.5 1876.12  5872.2 1878.75  5893.1 1878.96  5964.3 1883.13
  6027.9 1885.23  6035.5 1886.16  6056.4 1886.97  6060.1 1887.81  6063.5 1887.81
#Mann=3,-1,0
  4237.2    0.05       0  5051.2    0.03       0  5062.6    0.05       0
Bank Sta=5051.2,5062.6
Exp/Cntr=0.3,0.1

Type RM Length L Ch R = 1,49894,469,469,469
BEGIN DESCRIPTION:
South Prong Long Creek 90.0
END DESCRIPTION:
XS GIS Cut Line= 3
      1656755.00      6897038.00      1657155.00      6897438.00
      1657955.01      6898038.01
#Sta/Elev= 30
  4434.6 1875.75  4462.9 1874.77  4547.7 1870.10  4646.7 1865.99  4745.7 1858.35
  4774.0 1857.69  4873.0 1857.49  4915.4 1855.90  4957.9 1855.58  4972.0 1854.05
  4980.4 1851.50  4980.9 1851.00  4991.3 1851.00  4991.8 1851.50  5013.8 1852.00
  5036.7 1853.72  5157.6 1859.22  5186.7 1858.86  5250.3 1859.88  5336.7 1859.84
  5443.0 1861.65  5472.2 1862.71  5493.0 1862.63  5550.3 1864.63  5736.7 1868.68
  5822.2 1871.47  5863.8 1873.74  5913.8 1875.24  5978.4 1878.93  6000.3 1879.43
#Mann=3,-1,0
  4434.6    0.05       0  4980.4    0.03       0  4991.8    0.05       0
Bank Sta=4980.4,4991.8
Exp/Cntr=0.3,0.1

Type RM Length L Ch R = 1,49425,435,435,435
BEGIN DESCRIPTION:
South Prong Long Creek 89.0
END DESCRIPTION:
XS GIS Cut Line= 3
      1656454.97      6897437.97      1656855.00      6897788.00
      1657655.05      6898088.02
#Sta/Elev= 30
  4468.6 1871.56  4561.2 1867.81  4582.1 1865.68  4596.3 1865.31  4610.5 1863.82
  4667.5 1860.94  4681.2 1859.10  4737.7 1854.77  4766.2 1854.17  4837.4 1855.10
  4915.2 1854.79  4936.1 1853.64  4950.3 1851.24  4957.9 1850.74  4972.2 1851.02
  4987.3 1850.42  4987.8 1849.92  4998.3 1849.92  4998.8 1850.42  5032.2 1853.69
  5107.0 1857.39  5171.0 1857.95  5192.4 1857.45  5211.1 1857.98  5341.9 1857.80
  5363.3 1858.53  5412.2 1858.20  5613.4 1861.86  5759.3 1865.37  5854.6 1868.89
#Mann=3,-1,0
  4468.6    0.05       0  4987.3    0.03       0  4998.8    0.05       0
Bank Sta=4987.3,4998.8
Exp/Cntr=0.3,0.1