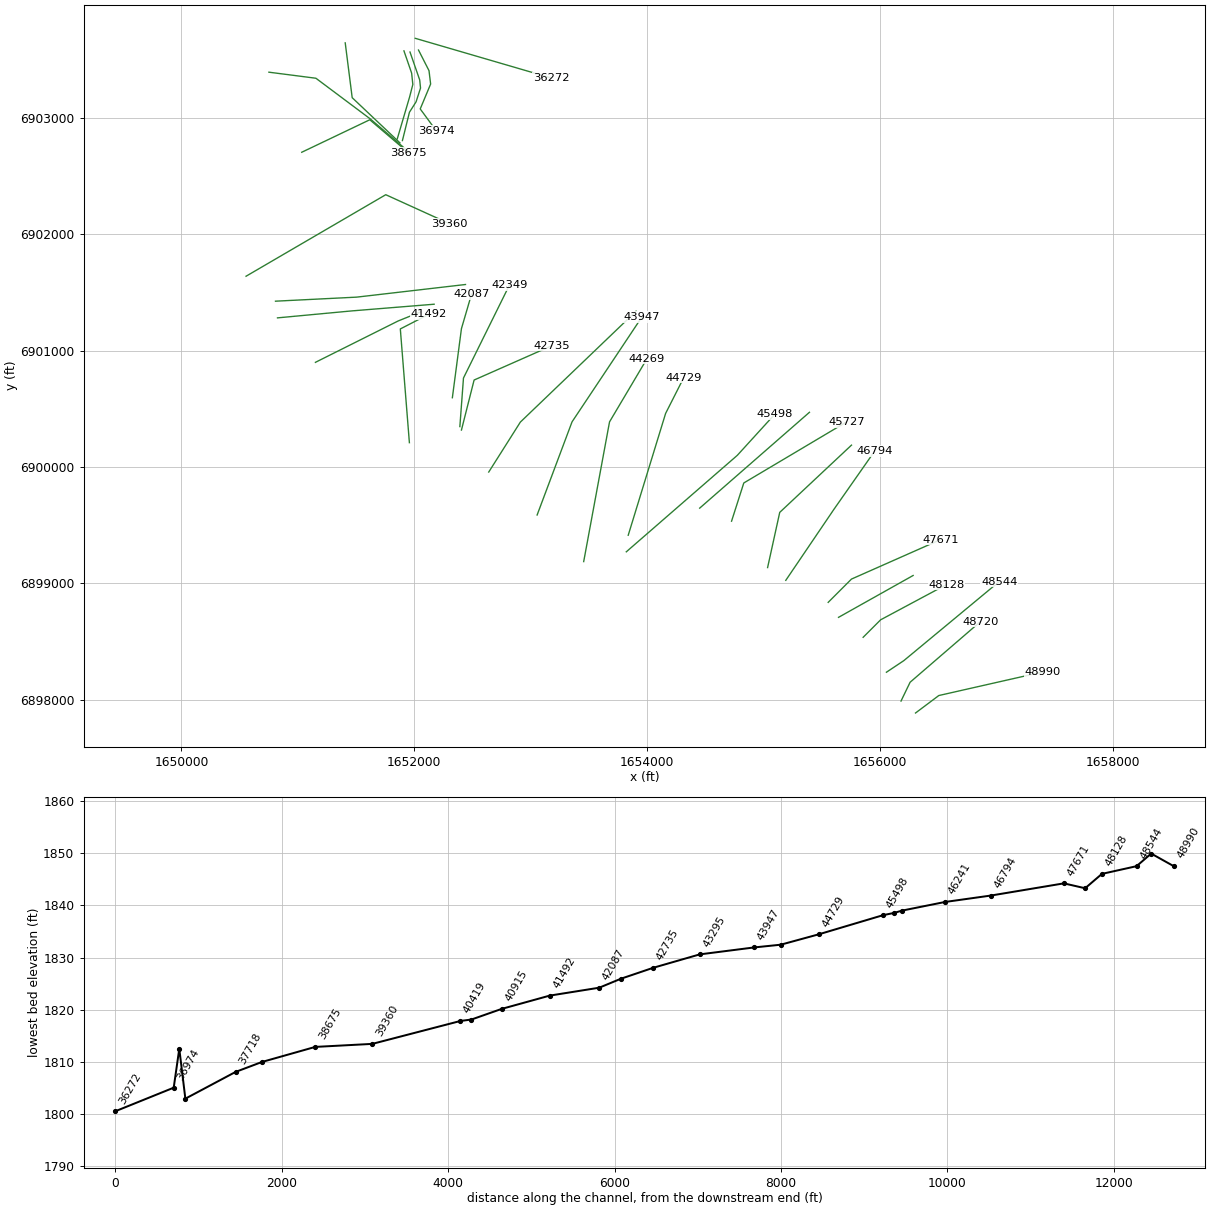
HEC-RAS study South Prong Long Creek.prj: South Prong Long Creek Base Level Engineering

--- South Prong Long Creek.g01 (geometry) --- (continued)

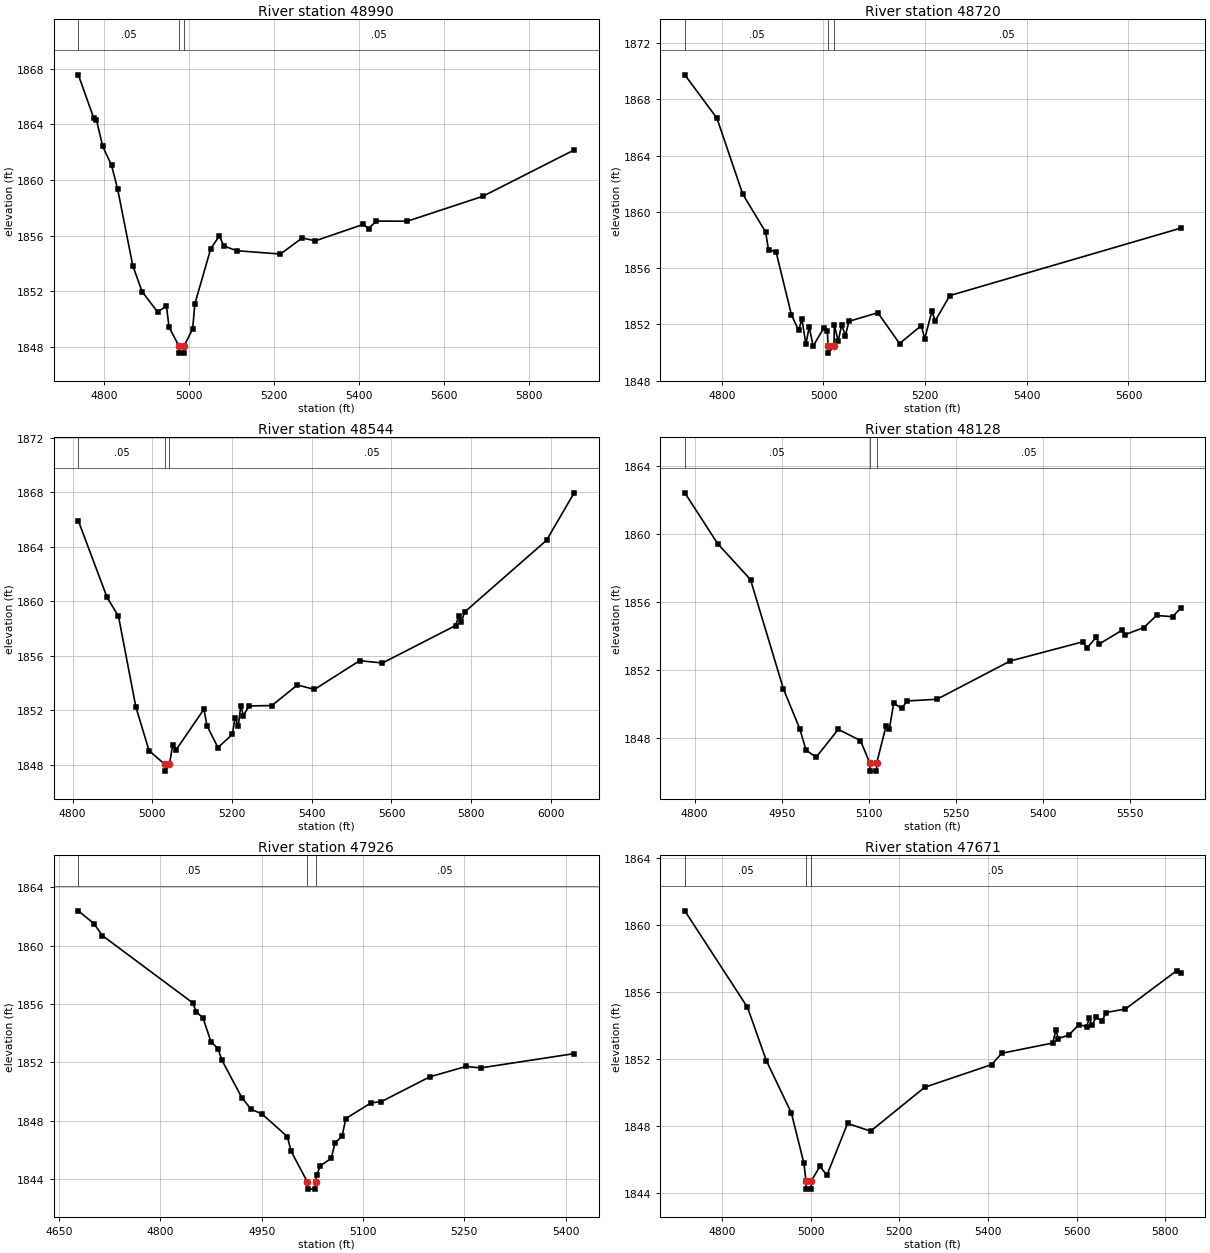
Type RM Length L Ch R = 1,48990,270,270,270
BEGIN DESCRIPTION:
South Prong Long Creek 88.0
END DESCRIPTION:
XS GIS Cut Line= 3
      1656305.00      6897888.00      1656505.00      6898038.00
      1657399.02      6898240.65
#Sta/Elev= 30
  4739.1 1867.55  4775.6 1864.42  4781.8 1864.31  4796.4 1862.41  4817.2 1861.05
  4831.8 1859.31  4867.2 1853.84  4889.1 1851.97  4925.6 1850.51  4946.4 1850.94
  4952.6 1849.41  4976.1 1848.05  4976.6 1847.55  4987.1 1847.55  4987.6 1848.05
  5008.1 1849.28  5013.2 1851.08  5050.6 1855.05  5071.1 1855.98  5081.4 1855.25
  5112.1 1854.91  5214.7 1854.67  5266.0 1855.83  5296.7 1855.62  5409.5 1856.80
  5421.9 1856.50  5440.3 1857.04  5513.2 1857.03  5690.9 1858.82  5905.8 1862.15
#Mann=3,-1,0
  4739.1    0.05       0  4976.1    0.05       0  4987.6    0.05       0
Bank Sta=4976.1,4987.6
Exp/Cntr=0.3,0.1

Type RM Length L Ch R = 1,48720,176,176,176
BEGIN DESCRIPTION:
Mapping XS 6bd10311
END DESCRIPTION:
XS GIS Cut Line= 3
      1656180.27      6897990.61      1656258.41      6898152.11
      1656861.30      6898671.84
#Sta/Elev= 30
  4727.2 1869.74  4790.4 1866.66  4841.2 1861.26  4886.3 1858.56  4891.9 1857.29
  4906.6 1857.18  4936.9 1852.69  4951.1 1851.58  4957.7 1852.37  4965.4 1850.60
  4972.0 1851.82  4979.6 1850.46  5000.5 1851.74  5007.7 1851.52  5009.0 1850.46
  5009.5 1849.96  5020.6 1850.46  5021.4 1851.96  5029.0 1850.80  5035.6 1851.97
  5043.3 1851.20  5049.9 1852.22  5106.9 1852.83  5149.7 1850.64  5192.5 1851.92
  5199.1 1850.99  5213.3 1852.93  5219.9 1852.26  5248.5 1854.05  5702.6 1858.84
#Mann=3,-1,0
  4727.2    0.05       0  5009.0    0.03       0  5020.6    0.05       0
Bank Sta=5009,5020.6
Exp/Cntr=0.3,0.1

Type RM Length L Ch R = 1,48544,416,416,416
BEGIN DESCRIPTION:
South Prong Long Creek 87.0
END DESCRIPTION:
XS GIS Cut Line= 3
      1656054.97      6898237.98      1656205.00      6898338.00
      1657024.03      6899016.69
#Sta/Elev= 30
  4814.4 1865.90  4886.5 1860.28  4915.1 1858.90  4958.7 1852.25  4991.7 1849.05
  5031.2 1848.04  5031.7 1847.54  5042.9 1848.04  5051.4 1849.48  5059.2 1849.08
  5129.5 1852.08  5137.3 1850.86  5164.7 1849.27  5201.1 1850.24  5207.6 1851.47
  5215.5 1850.82  5222.0 1852.35  5228.5 1851.61  5242.8 1852.32  5300.1 1852.35
  5363.9 1853.86  5406.9 1853.53  5520.2 1855.64  5577.5 1855.47  5761.1 1858.22
  5769.0 1858.93  5775.5 1858.45  5783.3 1859.20  5989.1 1864.47  6058.4 1867.95
#Mann=3,-1,0
  4814.4    0.05       0  5031.2    0.03       0  5042.9    0.05       0
Bank Sta=5031.2,5042.9
Exp/Cntr=0.3,0.1

Type RM Length L Ch R = 1,48128,202,202,202
BEGIN DESCRIPTION:
South Prong Long Creek 86.0
END DESCRIPTION:
XS GIS Cut Line= 3
      1655855.03      6898538.03      1656005.00      6898688.00
      1656570.43      6898990.40
#Sta/Elev= 30
  4783.3 1862.44  4839.8 1859.45  4896.4 1857.33  4953.0 1850.90  4981.2 1848.55
  4991.8 1847.31  5009.2 1846.87  5047.4 1848.52  5085.6 1847.86  5101.4 1846.56
  5101.9 1846.06  5113.2 1846.06  5113.7 1846.56  5129.5 1848.69  5135.2 1848.52
  5142.8 1850.05  5157.1 1849.75  5165.5 1850.19  5217.3 1850.29  5343.3 1852.54
  5469.2 1853.68  5474.9 1853.28  5491.2 1853.93  5496.9 1853.55  5535.1 1854.34
  5540.7 1854.09  5573.3 1854.51  5595.2 1855.22  5622.8 1855.15  5636.6 1855.65
#Mann=3,-1,0
  4783.3    0.05       0  5101.4    0.03       0  5113.7    0.05       0
Bank Sta=5101.4,5113.7
Exp/Cntr=0.3,0.1

Type RM Length L Ch R = 1,47926,255,255,255
BEGIN DESCRIPTION:
Mapping XS 3f685c61
END DESCRIPTION:
XS GIS Cut Line= 2
      1655643.84      6898709.41      1656284.43      6899068.76
#Sta/Elev= 30
  4678.3 1862.38  4701.5 1861.50  4714.0 1860.68  4847.5 1856.08  4853.3 1855.45
  4863.1 1855.02  4874.9 1853.39  4885.2 1852.94  4890.9 1852.15  4920.4 1849.58
  4934.3 1848.77  4950.2 1848.46  4987.9 1846.90  4993.6 1845.89  5017.5 1843.80
  5018.0 1843.30  5029.3 1843.30  5029.8 1843.80  5031.2 1844.26  5037.0 1844.91
  5052.9 1845.41  5058.6 1846.48  5068.9 1846.91  5074.6 1848.14  5112.2 1849.22
  5126.8 1849.29  5199.0 1851.00  5252.6 1851.71  5274.3 1851.61  5412.8 1852.59
#Mann=3,-1,0
  4678.3    0.05       0  5017.5    0.03       0  5029.8    0.05       0
Bank Sta=5017.5,5029.8
Exp/Cntr=0.3,0.1

Type RM Length L Ch R = 1,47671,877,877,877
BEGIN DESCRIPTION:
South Prong Long Creek 85.0
END DESCRIPTION:
XS GIS Cut Line= 3
      1655554.99      6898837.99      1655755.00      6899038.00
      1656518.87      6899376.09
#Sta/Elev= 30
  4716.3 1860.85  4857.7 1855.09  4900.2 1851.91  4956.7 1848.78  4985.0 1845.77
  4989.5 1844.74  4990.0 1844.24  5001.3 1844.24  5001.8 1844.74  5021.0 1845.60
  5036.8 1845.07  5083.4 1848.16  5135.4 1847.70  5257.4 1850.32  5408.0 1851.67
  5431.3 1852.35  5545.9 1852.96  5553.2 1853.71  5558.7 1853.23  5582.0 1853.43
  5605.3 1854.06  5622.5 1853.94  5628.6 1854.47  5634.0 1854.01  5644.4 1854.51
  5657.3 1854.27  5666.2 1854.78  5710.0 1854.99  5825.8 1857.28  5834.5 1857.11
#Mann=3,-1,0
  4716.3    0.05       0  4989.5    0.03       0  5001.8    0.05       0
Bank Sta=4989.5,5001.8
Exp/Cntr=0.3,0.1

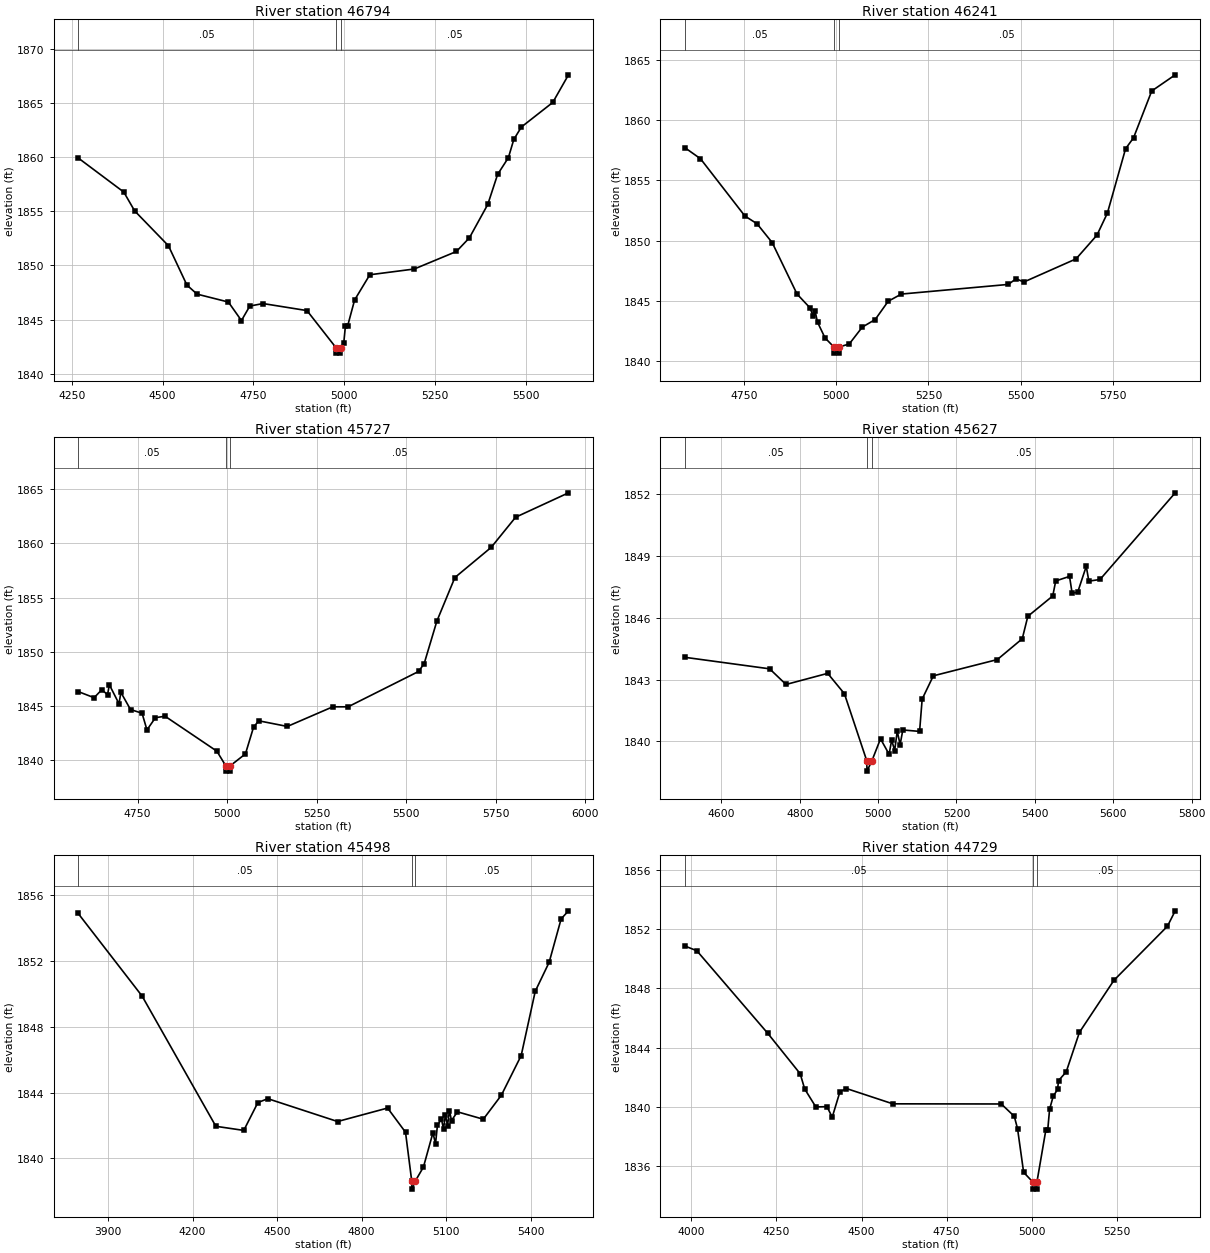
Type RM Length L Ch R = 1,46794,553,553,553
BEGIN DESCRIPTION:
South Prong Long Creek 84.0
END DESCRIPTION:
XS GIS Cut Line= 3
      1655190.69      6899027.08      1655605.00      6899638.00
      1655955.01      6900138.01
#Sta/Elev= 30
  4267.7 1859.94  4393.4 1856.78  4423.3 1855.04  4516.2 1851.82  4567.1 1848.18
  4595.0 1847.35  4681.0 1846.62  4716.9 1844.91  4740.0 1846.25  4776.3 1846.48
  4897.1 1845.83  4977.0 1842.40  4977.5 1841.90  4989.3 1841.90  4989.8 1842.40
  4998.4 1842.88  5002.8 1844.41  5008.9 1844.41  5028.1 1846.81  5069.9 1849.14
  5192.0 1849.67  5308.0 1851.29  5343.7 1852.55  5394.3 1855.64  5421.3 1858.41
  5451.0 1859.96  5465.8 1861.64  5486.7 1862.79  5573.0 1865.06  5616.2 1867.61
#Mann=3,-1,0
  4267.7    0.05       0  4977.0    0.03       0  4989.8    0.05       0
Bank Sta=4977,4989.8
Exp/Cntr=0.3,0.1

Type RM Length L Ch R = 1,46241,514,514,514
BEGIN DESCRIPTION:
South Prong Long Creek 83.0
END DESCRIPTION:
XS GIS Cut Line= 3
      1655034.46      6899136.53      1655138.62      6899610.44
      1655754.99      6900187.99
#Sta/Elev= 30
  4589.3 1857.71  4631.8 1856.79  4752.2 1852.04  4785.3 1851.39  4826.3 1849.83
  4893.7 1845.56  4928.7 1844.42  4937.5 1843.73  4942.6 1844.14  4949.2 1843.23
  4969.6 1841.92  4994.0 1841.16  4994.5 1840.66  5006.3 1840.66  5006.8 1841.16
  5035.3 1841.42  5070.7 1842.82  5105.7 1843.45  5140.8 1844.96  5176.5 1845.56
  5466.6 1846.36  5487.7 1846.83  5508.7 1846.56  5650.3 1848.48  5707.0 1850.45
  5735.3 1852.28  5784.6 1857.62  5806.1 1858.52  5855.5 1862.41  5919.2 1863.75
#Mann=3,-1,0
  4589.3    0.05       0  4994.0    0.03       0  5006.8    0.05       0
Bank Sta=4994,5006.8
Exp/Cntr=0.3,0.1

Type RM Length L Ch R = 1,45727,100,100,100
BEGIN DESCRIPTION:
South Prong Long Creek 82.0
END DESCRIPTION:
XS GIS Cut Line= 3
      1654724.89      6899534.90      1654830.00      6899863.00
      1655710.78      6900386.04
#Sta/Elev= 30
  4583.8 1846.35  4628.6 1845.78  4650.1 1846.52  4666.0 1846.06  4671.2 1846.97
  4698.1 1845.22  4703.3 1846.27  4730.2 1844.69  4762.4 1844.35  4776.1 1842.81
  4799.8 1843.94  4826.7 1844.07  4971.2 1840.85  4995.9 1839.51  4996.4 1839.01
  5008.3 1839.01  5008.8 1839.51  5051.0 1840.60  5073.7 1843.07  5088.1 1843.65
  5168.0 1843.13  5294.7 1844.94  5337.5 1844.94  5534.3 1848.20  5549.9 1848.93
  5585.4 1852.85  5635.6 1856.86  5736.9 1859.64  5805.1 1862.42  5952.7 1864.67
#Mann=3,-1,0
  4583.8    0.05       0  4995.9    0.03       0  5008.8    0.05       0
Bank Sta=4995.9,5008.8
Exp/Cntr=0.3,0.1

Type RM Length L Ch R = 1,45627,129,129,129
BEGIN DESCRIPTION:
Mapping XS 44582191
END DESCRIPTION:
XS GIS Cut Line= 2
      1654451.11      6899646.89      1655393.85      6900469.84
#Sta/Elev= 30
  4506.7 1844.08  4723.2 1843.52  4765.0 1842.76  4871.3 1843.30  4914.0 1842.31
  4971.1 1839.05  4971.6 1838.55  4984.1 1839.05  5006.1 1840.12  5028.0 1839.37
  5034.6 1840.06  5042.2 1839.55  5048.8 1840.49  5056.1 1839.84  5063.1 1840.55
  5105.8 1840.48  5112.4 1842.05  5140.9 1843.18  5304.2 1843.97  5367.8 1844.98
  5382.0 1846.07  5445.6 1847.06  5453.2 1847.79  5488.4 1848.01  5495.0 1847.20
  5509.2 1847.24  5531.1 1848.50  5537.7 1847.78  5566.2 1847.86  5758.1 1852.07
#Mann=3,-1,0
  4506.7    0.05       0  4971.1    0.03       0  4984.1    0.05       0
Bank Sta=4971.1,4984.1
Exp/Cntr=0.3,0.1

Type RM Length L Ch R = 1,45498,769,769,769
BEGIN DESCRIPTION:
South Prong Long Creek 81.0
END DESCRIPTION:
XS GIS Cut Line= 3
      1653820.93      6899271.92      1654774.04      6900100.03
      1655096.42      6900453.61
#Sta/Elev= 30
  3793.5 1854.90  4020.7 1849.87  4282.7 1841.95  4381.8 1841.70  4431.8 1843.39
  4466.9 1843.63  4714.8 1842.24  4892.4 1843.06  4956.0 1841.59  4978.0 1838.63
  4978.5 1838.13  4991.0 1838.63  5019.6 1839.47  5053.4 1841.56  5062.5 1840.88
  5069.3 1842.01  5083.5 1842.38  5090.9 1841.80  5097.7 1842.64  5105.1 1841.99
  5111.9 1842.90  5119.3 1842.30  5140.3 1842.83  5232.1 1842.38  5296.3 1843.84
  5366.6 1846.25  5416.6 1850.16  5465.9 1851.92  5508.5 1854.56  5534.6 1855.05
#Mann=3,-1,0
  3793.5    0.05       0  4978.0    0.03       0  4991.0    0.05       0
Bank Sta=4978,4991
Exp/Cntr=0.3,0.1

Type RM Length L Ch R = 1,44729,460,460,460
BEGIN DESCRIPTION:
South Prong Long Creek 80.0
END DESCRIPTION:
XS GIS Cut Line= 3
      1653837.39      6899414.23      1654158.58      6900460.27
      1654314.81      6900768.39
#Sta/Elev= 30
  3981.2 1850.86  4016.5 1850.54  4224.5 1844.98  4319.9 1842.25  4333.2 1841.22
  4365.9 1840.01  4398.6 1840.03  4414.0 1839.32  4436.6 1841.03  4455.9 1841.25
  4591.9 1840.22  4910.4 1840.21  4948.4 1839.38  4958.0 1838.55  4975.9 1835.60
  5002.1 1834.97  5002.6 1834.47  5014.6 1834.47  5015.1 1834.97  5041.3 1838.48
  5046.6 1838.45  5052.1 1839.85  5062.6 1840.72  5075.4 1841.19  5078.5 1841.79
  5100.8 1842.37  5139.7 1845.04  5241.1 1848.55  5398.0 1852.19  5420.9 1853.23
#Mann=3,-1,0
  3981.2    0.05       0  5002.1    0.03       0  5015.1    0.05       0
Bank Sta=5002.1,5015.1
Exp/Cntr=0.3,0.1

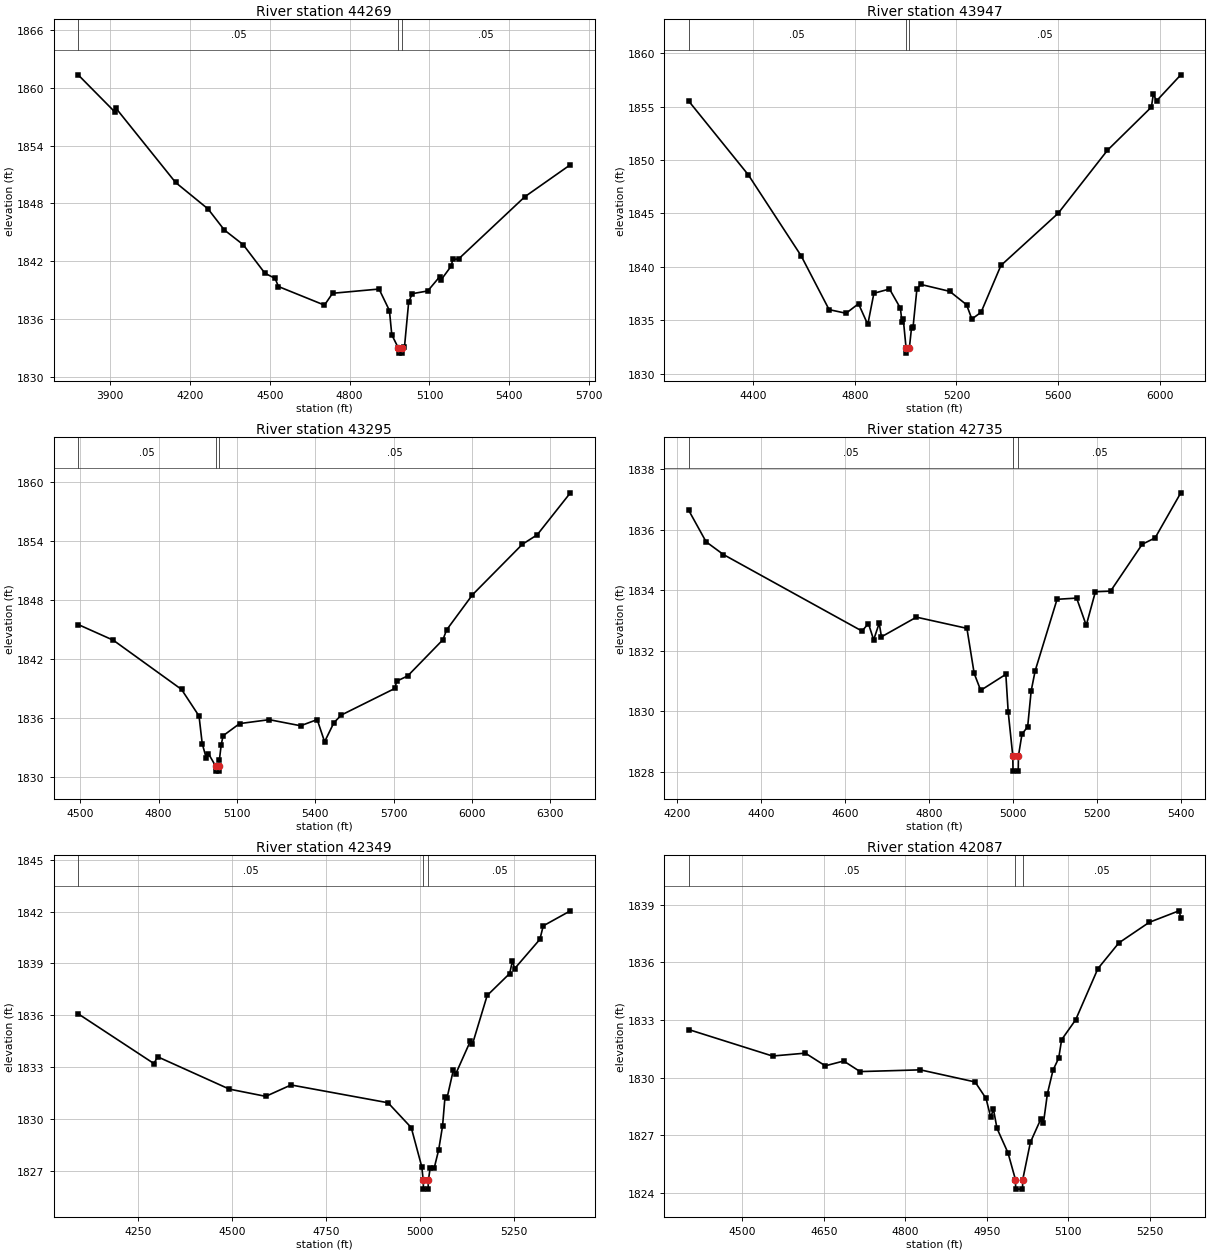
Type RM Length L Ch R = 1,44269,322,322,322
BEGIN DESCRIPTION:
South Prong Long Creek 79.0
END DESCRIPTION:
XS GIS Cut Line= 3
      1653455.00      6899188.00      1653676.86      6900387.55
      1653997.98      6900928.99
#Sta/Elev= 30
  3780.1 1861.34  3917.5 1857.50  3922.6 1857.86  4146.2 1850.17  4268.2 1847.42
  4329.3 1845.24  4400.4 1843.71  4481.8 1840.75  4519.9 1840.22  4532.7 1839.37
  4705.5 1837.44  4736.0 1838.67  4910.6 1839.11  4949.6 1836.88  4958.5 1834.36
  4983.7 1832.96  4984.2 1832.46  4996.3 1832.46  4996.8 1832.96  5006.2 1833.11
  5021.9 1837.75  5035.4 1838.63  5093.5 1838.91  5138.8 1840.40  5144.6 1840.10
  5181.7 1841.49  5187.5 1842.19  5209.8 1842.24  5458.4 1848.69  5629.5 1852.01
#Mann=3,-1,0
  3780.1    0.05       0  4983.7    0.03       0  4996.8    0.05       0
Bank Sta=4983.7,4996.8
Exp/Cntr=0.3,0.1

Type RM Length L Ch R = 1,43947,652,652,652
BEGIN DESCRIPTION:
South Prong Long Creek 78.0
END DESCRIPTION:
XS GIS Cut Line= 3
      1653054.99      6899587.97      1653355.00      6900388.00
      1653955.00      6901288.01
#Sta/Elev= 30
  4146.5 1855.53  4381.5 1848.61  4588.9 1841.05  4699.2 1836.00  4766.0 1835.66
  4814.9 1836.55  4851.4 1834.61  4875.4 1837.53  4936.8 1837.93  4979.6 1836.14
  4985.8 1834.88  4991.1 1835.08  5001.9 1832.43  5002.4 1831.93  5015.0 1832.43
  5023.5 1834.31  5029.5 1834.38  5044.5 1837.90  5059.5 1838.36  5173.7 1837.71
  5239.8 1836.46  5260.8 1835.12  5296.9 1835.75  5375.0 1840.13  5600.4 1845.02
  5794.1 1850.91  5966.9 1854.95  5974.4 1856.13  5987.9 1855.55  6082.6 1857.97
#Mann=3,-1,0
  4146.5    0.05       0  5001.9    0.05       0  5015.0    0.05       0
Bank Sta=5001.9,5015
Exp/Cntr=0.3,0.1

Type RM Length L Ch R = 1,43295,560,560,560
BEGIN DESCRIPTION:
South Prong Long Creek 77.0
END DESCRIPTION:
XS GIS Cut Line= 3
      1652639.51      6899956.84      1652911.08      6900385.80
      1653904.98      6901337.98
#Sta/Elev= 30
  4492.3 1845.53  4626.9 1843.93  4888.0 1838.92  4955.0 1836.21  4967.1 1833.41
  4982.1 1831.98  4990.8 1832.39  5018.8 1831.10  5019.3 1830.60  5031.7 1830.60
  5032.2 1831.10  5032.8 1831.72  5039.7 1833.24  5046.9 1834.20  5110.4 1835.44
  5223.7 1835.84  5343.8 1835.22  5407.3 1835.85  5435.6 1833.59  5471.2 1835.53
  5499.5 1836.31  5704.5 1839.02  5711.7 1839.76  5753.9 1840.30  5888.5 1843.98
  5902.6 1844.98  6001.7 1848.56  6192.6 1853.70  6249.2 1854.66  6376.4 1858.94
#Mann=3,-1,0
  4492.3    0.05       0  5018.8    0.05       0  5032.2    0.05       0
Bank Sta=5018.8,5032.2
Exp/Cntr=0.3,0.1

Type RM Length L Ch R = 1,42735,386,386,386
BEGIN DESCRIPTION:
Mapping XS 69447e92
END DESCRIPTION:
XS GIS Cut Line= 3
      1652405.07      6900317.52      1652513.62      6900746.73
      1653181.03      6901041.43
#Sta/Elev= 30
  4228.1 1836.65  4269.9 1835.60  4311.1 1835.18  4641.2 1832.65  4656.4 1832.90
  4668.9 1832.36  4682.1 1832.91  4687.5 1832.46  4770.7 1833.11  4891.0 1832.74
  4908.3 1831.25  4923.8 1830.69  4983.7 1831.22  4989.3 1829.98  5000.3 1828.52
  5000.8 1828.02  5013.2 1828.02  5013.7 1828.52  5022.1 1829.24  5035.7 1829.49
  5044.0 1830.67  5053.6 1831.34  5105.7 1833.70  5152.3 1833.74  5175.2 1832.84
  5197.0 1833.95  5233.1 1833.97  5308.5 1835.52  5339.2 1835.73  5400.4 1837.22
#Mann=3,-1,0
  4228.1    0.05       0  5000.3    0.03       0  5013.7    0.05       0
Bank Sta=5000.3,5013.7
Exp/Cntr=0.3,0.1

Type RM Length L Ch R = 1,42349,262,262,262
BEGIN DESCRIPTION:
Mapping XS 74ede5fc
END DESCRIPTION:
XS GIS Cut Line= 3
      1652391.39      6900347.11      1652422.47      6900764.09
      1652817.45      6901562.72
#Sta/Elev= 30
  4091.4 1836.08  4292.8 1833.20  4302.9 1833.59  4493.4 1831.72  4590.3 1831.30
  4657.6 1831.96  4915.5 1830.93  4977.3 1829.49  5005.3 1827.22  5009.2 1826.43
  5009.7 1825.93  5022.2 1825.93  5022.7 1826.43  5027.7 1827.16  5038.2 1827.14
  5050.2 1828.20  5060.6 1829.59  5067.0 1831.26  5072.6 1831.22  5089.4 1832.84
  5095.0 1832.57  5134.3 1834.49  5139.9 1834.31  5179.2 1837.14  5239.0 1838.41
  5246.5 1839.15  5252.1 1838.69  5319.4 1840.39  5328.3 1841.17  5400.5 1842.04
#Mann=3,-1,0
  4091.4    0.05       0  5009.2    0.03       0  5022.7    0.05       0
Bank Sta=5009.2,5022.7
Exp/Cntr=0.3,0.1

Type RM Length L Ch R = 1,42087,595,595,595
BEGIN DESCRIPTION:
South Prong Long Creek 76.0
END DESCRIPTION:
XS GIS Cut Line= 3
      1652326.98      6900594.77      1652405.00      6901188.00
      1652491.70      6901483.82
#Sta/Elev= 30
  4400.8 1832.51  4555.4 1831.13  4615.9 1831.28  4652.6 1830.62  4686.5 1830.87
  4716.7 1830.32  4827.7 1830.41  4928.5 1829.78  4948.7 1828.92  4957.3 1827.94
  4962.3 1828.36  4968.9 1827.36  4989.1 1826.09  5002.8 1824.70  5003.3 1824.20
  5015.8 1824.20  5016.3 1824.70  5030.4 1826.64  5049.3 1827.83  5054.5 1827.66
  5061.7 1829.17  5072.1 1830.40  5082.5 1831.02  5087.9 1831.98  5113.8 1833.02
  5154.7 1835.68  5193.3 1837.02  5249.2 1838.09  5304.0 1838.69  5307.4 1838.34
#Mann=3,-1,0
  4400.8    0.05       0  5002.8    0.05       0  5016.3    0.05       0
Bank Sta=5002.8,5016.3
Exp/Cntr=0.3,0.1

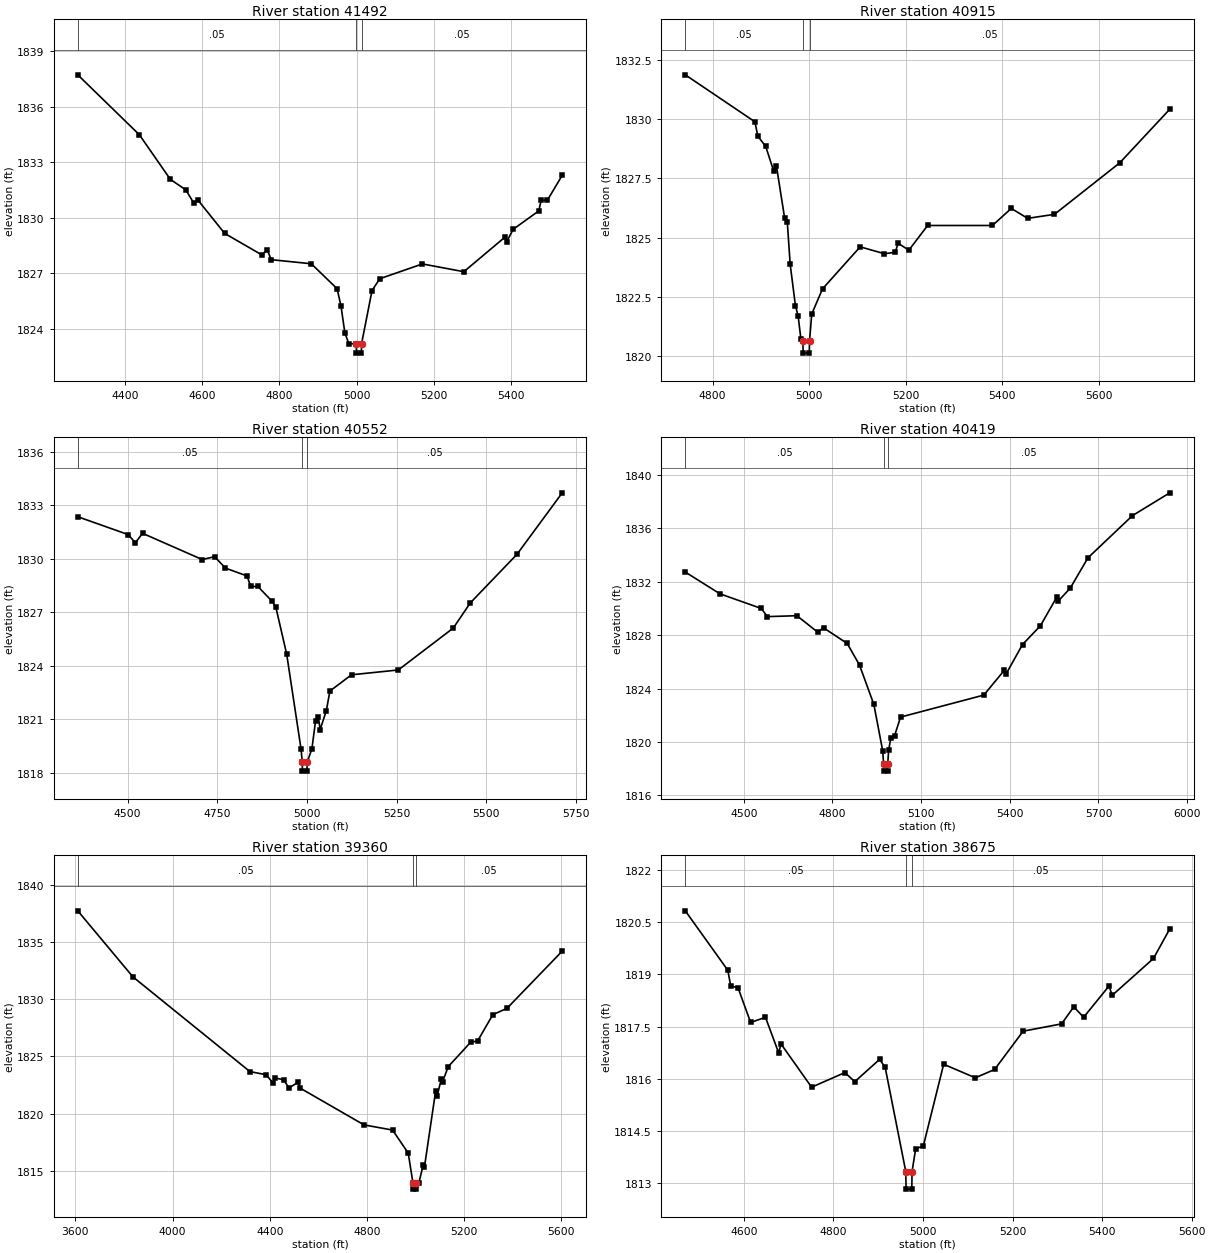
Type RM Length L Ch R = 1,41492,577,577,577
BEGIN DESCRIPTION:
Mapping XS c6c2dae3
END DESCRIPTION:
XS GIS Cut Line= 4
      1651957.89      6900209.14      1651923.34      6900642.56
      1651880.06      6901185.60      1652123.71      6901310.60
#Sta/Elev= 30
  4278.2 1837.72  4437.6 1834.48  4517.8 1832.07  4557.9 1831.50  4578.0 1830.80
  4588.0 1830.98  4658.3 1829.15  4754.3 1827.99  4768.6 1828.26  4778.6 1827.73
  4882.4 1827.51  4949.2 1826.16  4959.2 1825.23  4969.2 1823.78  4979.3 1823.20
  4998.8 1823.18  4999.3 1822.68  5011.9 1822.68  5012.4 1823.18  5039.5 1826.06
  5059.5 1826.70  5169.9 1827.50  5277.1 1827.08  5382.4 1828.93  5388.0 1828.70
  5404.6 1829.37  5471.2 1830.37  5476.9 1830.94  5493.4 1830.95  5531.6 1832.29
#Mann=3,-1,0
  4278.2    0.05       0  4998.8    0.05       0  5012.4    0.05       0
Bank Sta=4998.8,5012.4
Exp/Cntr=0.3,0.1

Type RM Length L Ch R = 1,40915,363,363,363
BEGIN DESCRIPTION:
Mapping XS 57628458
END DESCRIPTION:
XS GIS Cut Line= 3
      1651150.76      6900898.63      1651860.88      6901253.69
      1652055.19      6901332.18
#Sta/Elev= 30
  4743.6 1831.86  4887.8 1829.88  4893.7 1829.28  4910.2 1828.84  4926.9 1827.79
  4932.5 1828.00  4949.3 1825.83  4954.9 1825.65  4960.8 1823.88  4971.7 1822.13
  4977.3 1821.70  4983.1 1820.71  4987.2 1820.63  4987.7 1820.13  5000.4 1820.13
  5000.9 1820.63  5005.5 1821.78  5027.9 1822.84  5105.8 1824.61  5156.1 1824.32
  5178.5 1824.38  5184.4 1824.76  5206.7 1824.47  5245.6 1825.51  5379.8 1825.51
  5418.9 1826.23  5452.7 1825.81  5508.3 1825.98  5643.5 1828.15  5747.1 1830.41
#Mann=3,-1,0
  4743.6    0.05       0  4987.2    0.03       0  5000.9    0.05       0
Bank Sta=4987.2,5000.9
Exp/Cntr=0.3,0.1

Type RM Length L Ch R = 1,40552,133,133,133
BEGIN DESCRIPTION:
South Prong Long Creek 75.0
END DESCRIPTION:
XS GIS Cut Line= 3
      1650825.20      6901280.58      1651461.12      6901340.18
      1652170.38      6901397.74
#Sta/Elev= 30
  4361.3 1832.35  4501.7 1831.35  4521.8 1830.89  4541.9 1831.42  4708.2 1829.95
  4742.8 1830.11  4772.9 1829.47  4833.2 1829.03  4843.2 1828.44  4863.3 1828.44
  4903.5 1827.60  4913.5 1827.27  4943.6 1824.65  4983.8 1819.31  4987.0 1818.59
  4987.5 1818.09  5000.2 1818.09  5000.7 1818.59  5013.9 1819.34  5024.0 1820.89
  5031.9 1821.13  5036.9 1820.42  5054.1 1821.48  5064.1 1822.58  5124.3 1823.49
  5254.7 1823.76  5408.0 1826.11  5455.4 1827.52  5585.8 1830.25  5711.6 1833.69
#Mann=3,-1,0
  4361.3    0.05       0  4987.0    0.05       0  5000.7    0.05       0
Bank Sta=4987,5000.7
Exp/Cntr=0.3,0.1

Type RM Length L Ch R = 1,40419,1059,1059,1059
BEGIN DESCRIPTION:
South Prong Long Creek 74.0
END DESCRIPTION:
XS GIS Cut Line= 3
      1650807.90      6901423.81      1651504.94      6901458.57
      1652439.87      6901567.04
#Sta/Elev= 30
  4302.1 1832.73  4419.3 1831.10  4559.5 1830.00  4579.5 1829.39  4679.7 1829.46
  4749.8 1828.23  4769.8 1828.55  4849.9 1827.38  4891.5 1825.76  4940.0 1822.81
  4970.0 1819.33  4973.1 1818.31  4973.6 1817.81  4986.4 1817.81  4986.9 1818.31
  4990.0 1819.36  4997.5 1820.32  5010.1 1820.46  5030.3 1821.86  5312.1 1823.51
  5381.5 1825.37  5386.6 1825.06  5443.0 1827.30  5503.4 1828.70  5558.9 1830.85
  5563.9 1830.56  5604.1 1831.51  5664.5 1833.80  5814.9 1836.96  5941.2 1838.67
#Mann=3,-1,0
  4302.1    0.05       0  4973.1    0.03       0  4986.9    0.05       0
Bank Sta=4973.1,4986.9
Exp/Cntr=0.3,0.1

Type RM Length L Ch R = 1,39360,685,685,685
BEGIN DESCRIPTION:
South Prong Long Creek 73.0
END DESCRIPTION:
XS GIS Cut Line= 3
      1650555.02      6901638.01      1651755.00      6902338.00
      1652305.02      6902087.99
#Sta/Elev= 30
  3609.9 1837.72  3836.9 1831.95  4318.1 1823.68  4385.5 1823.40  4414.1 1822.65
  4420.3 1823.12  4457.1 1822.97  4478.6 1822.24  4515.8 1822.74  4524.5 1822.24
  4787.8 1819.02  4905.3 1818.57  4969.8 1816.55  4989.3 1813.91  4989.8 1813.41
  5002.7 1813.41  5003.2 1813.91  5013.4 1813.96  5031.0 1815.49  5036.5 1815.35
  5082.6 1822.00  5088.1 1821.51  5105.7 1823.01  5111.2 1822.80  5134.2 1824.11
  5226.5 1826.24  5255.1 1826.35  5317.7 1828.65  5375.9 1829.20  5603.3 1834.20
#Mann=3,-1,0
  3609.9    0.05       0  4989.3    0.05       0  5003.2    0.05       0
Bank Sta=4989.3,5003.2
Exp/Cntr=0.3,0.1

Type RM Length L Ch R = 1,38675,640,640,640
BEGIN DESCRIPTION:
Mapping XS 6f9800b5
END DESCRIPTION:
XS GIS Cut Line= 3
      1651033.49      6902702.45      1651617.88      6902981.57
      1651948.20      6902699.80
#Sta/Elev= 30
  4469.3 1820.83  4564.3 1819.12  4570.7 1818.67  4587.0 1818.62  4615.2 1817.62
  4648.3 1817.77  4677.7 1816.75  4683.2 1817.00  4751.3 1815.76  4825.6 1816.18
  4847.8 1815.92  4903.2 1816.56  4915.6 1816.33  4961.7 1813.33  4962.2 1812.83
  4975.1 1812.83  4975.6 1813.33  4983.7 1813.99  5000.8 1814.07  5046.2 1816.42
  5116.9 1816.03  5160.0 1816.27  5223.7 1817.37  5309.4 1817.58  5336.8 1818.07
  5358.8 1817.77  5415.5 1818.67  5422.5 1818.40  5514.7 1819.46  5551.1 1820.31
#Mann=3,-1,0
  4469.3    0.05       0  4961.7    0.05       0  4975.6    0.05       0
Bank Sta=4961.7,4975.6
Exp/Cntr=0.3,0.1

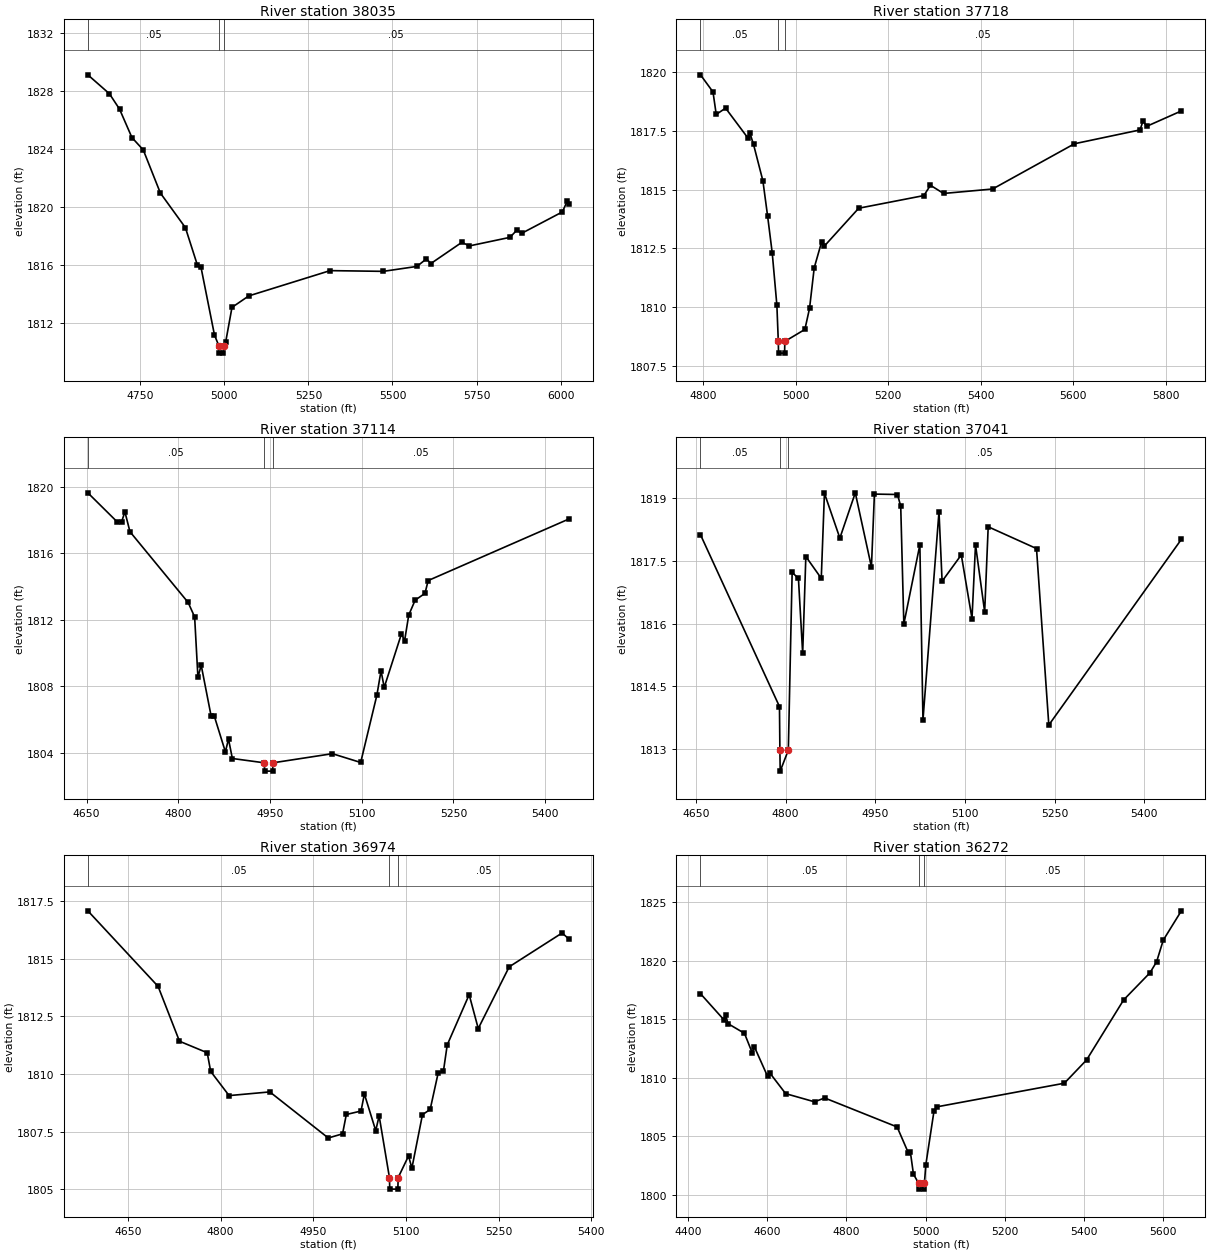
Type RM Length L Ch R = 1,38035,317,317,317
BEGIN DESCRIPTION:
South Prong Long Creek 72.0
END DESCRIPTION:
XS GIS Cut Line= 4
      1650751.42      6903389.96      1651155.00      6903338.00
      1651620.95      6902989.57      1651956.94      6902702.73
#Sta/Elev= 30
  4593.7 1829.10  4657.8 1827.80  4688.0 1826.74  4724.9 1824.78  4758.6 1823.93
  4809.5 1820.96  4883.9 1818.58  4919.9 1815.98  4930.0 1815.89  4970.4 1811.19
  4983.5 1810.44  4984.0 1809.94  4997.0 1809.94  4997.5 1810.44  5003.7 1810.70
  5022.5 1813.09  5072.5 1813.88  5314.3 1815.62  5472.7 1815.57  5572.7 1815.91
  5600.9 1816.43  5614.3 1816.11  5706.5 1817.57  5728.5 1817.32  5849.3 1817.91
  5870.1 1818.41  5884.4 1818.19  6005.2 1819.66  6019.4 1820.38  6024.2 1820.22
#Mann=3,-1,0
  4593.7    0.05       0  4983.5    0.03       0  4997.5    0.05       0
Bank Sta=4983.5,4997.5
Exp/Cntr=0.3,0.1

Type RM Length L Ch R = 1,37718,604,604,604
BEGIN DESCRIPTION:
Mapping XS f7277166
END DESCRIPTION:
XS GIS Cut Line= 3
      1651406.84      6903641.72      1651466.69      6903170.98
      1651876.63      6902783.09
#Sta/Elev= 30
  4794.7 1819.90  4821.7 1819.17  4828.7 1818.21  4848.9 1818.48  4896.6 1817.22
  4901.7 1817.40  4909.3 1816.93  4929.5 1815.38  4939.6 1813.89  4949.7 1812.30
  4959.7 1810.08  4962.8 1808.53  4963.3 1808.03  4976.4 1808.03  4976.9 1808.53
  5020.2 1809.04  5030.3 1809.94  5040.4 1811.67  5056.6 1812.79  5061.6 1812.58
  5136.5 1814.21  5277.3 1814.75  5291.5 1815.19  5319.8 1814.84  5425.8 1815.03
  5602.6 1816.96  5744.2 1817.55  5751.0 1817.94  5758.3 1817.70  5833.6 1818.36
#Mann=3,-1,0
  4794.7    0.05       0  4962.8    0.05       0  4976.9    0.05       0
Bank Sta=4962.8,4976.9
Exp/Cntr=0.3,0.1

Type RM Length L Ch R = 1,37114,73,73,73
BEGIN DESCRIPTION:
Mapping XS a8edb484
END DESCRIPTION:
XS GIS Cut Line= 5
      1651911.18      6903573.15      1651977.16      6903382.14
      1651987.58      6903284.92      1651959.80      6903177.28
      1651853.78      6902816.99
#Sta/Elev= 30
  4651.9 1819.64  4699.7 1817.90  4707.3 1817.91  4712.5 1818.50  4720.8 1817.30
  4816.0 1813.04  4826.6 1812.17  4832.0 1808.53  4837.3 1809.27  4853.5 1806.22
  4858.6 1806.22  4876.9 1804.05  4882.0 1804.82  4888.3 1803.65  4940.6 1803.39
  4941.1 1802.89  4954.2 1802.89  4954.7 1803.39  5051.9 1803.94  5098.2 1803.41
  5124.7 1807.46  5131.5 1808.93  5136.7 1807.93  5164.8 1811.14  5170.1 1810.75
  5176.8 1812.28  5187.3 1813.18  5203.4 1813.59  5208.6 1814.36  5438.5 1818.06
#Mann=3,-1,0
  4651.9    0.05       0  4940.6    0.05       0  4954.7    0.05       0
Bank Sta=4940.6,4954.7
Exp/Cntr=0.3,0.1

Type RM Length L Ch R = 1,37041,67,67,67
BEGIN DESCRIPTION:
Mapping XS 1d4f2cfa
END DESCRIPTION:
XS GIS Cut Line= 6
      1651963.26      6903562.75      1652046.61      6903323.12
      1652053.55      6903253.67      1652015.36      6903135.62
      1651958.36      6903045.94      1651898.09      6902802.84
#Sta/Elev= 30
  4657.6 1818.12  4789.7 1814.02  4790.4 1812.98  4790.9 1812.48  4804.5 1812.98
  4810.9 1817.22  4821.4 1817.08  4828.5 1815.29  4833.8 1817.60  4859.6 1817.08
  4864.9 1819.11  4890.7 1818.04  4916.5 1819.12  4943.5 1817.35  4948.5 1819.09
  4987.1 1819.08  4992.5 1818.80  4997.7 1815.99  5024.5 1817.88  5029.7 1813.70
  5056.5 1818.67  5061.7 1817.01  5093.8 1817.64  5111.7 1816.12  5117.6 1817.88
  5132.9 1816.28  5138.8 1818.31  5219.6 1817.79  5240.2 1813.58  5461.9 1818.01
#Mann=3,-1,0
  4657.6    0.05       0  4790.4    0.03       0  4804.5    0.05       0
Bank Sta=4790.4,4804.5
Exp/Cntr=0.3,0.1

Type RM Length L Ch R = 1,36974,702,702,702
BEGIN DESCRIPTION:
Mapping XS b3044e0b
END DESCRIPTION:
XS GIS Cut Line= 5
      1652036.17      6903580.09      1652126.47      6903402.98
      1652140.36      6903288.39      1652051.03      6903074.36
      1652188.42      6902887.35
#Sta/Elev= 30
  4585.1 1817.08  4698.8 1813.80  4733.4 1811.42  4778.3 1810.92  4783.9 1810.11
  4813.7 1809.06  4879.6 1809.22  4974.2 1807.22  4997.3 1807.40  5003.4 1808.24
  5027.2 1808.39  5032.6 1809.13  5051.0 1807.54  5056.5 1808.18  5073.2 1805.50
  5073.7 1805.00  5086.8 1805.00  5087.3 1805.50  5104.1 1806.44  5109.5 1805.91
  5126.6 1808.23  5139.1 1808.46  5152.1 1810.05  5160.5 1810.11  5166.7 1811.26
  5202.2 1813.44  5216.9 1811.97  5267.0 1814.65  5352.7 1816.12  5363.3 1815.86
#Mann=3,-1,0
  4585.1    0.05       0  5073.2    0.03       0  5087.3    0.05       0
Bank Sta=5073.2,5087.3
Exp/Cntr=0.3,0.1

Type RM Length L Ch R = 1,36272,508,508,508
BEGIN DESCRIPTION:
Mapping XS b80318c5
END DESCRIPTION:
XS GIS Cut Line= 2
      1652008.37      6903680.77      1653175.06      6903340.48
#Sta/Elev= 30
  4431.2 1817.19  4489.8 1814.98  4495.0 1815.35  4500.6 1814.63  4542.3 1813.80
  4562.0 1812.13  4567.2 1812.66  4600.7 1810.12  4605.9 1810.43  4646.4 1808.64
  4719.4 1807.94  4745.0 1808.27  4928.1 1805.79  4956.3 1803.59  4961.5 1803.67
  4969.4 1801.75  4982.5 1800.97  4983.0 1800.47  4996.6 1800.47  4997.1 1800.97
  5000.6 1802.54  5021.4 1807.17  5028.5 1807.51  5350.7 1809.53  5406.9 1811.52
  5500.6 1816.66  5567.2 1818.98  5583.9 1819.92  5600.7 1821.77  5646.5 1824.28
#Mann=3,-1,0
  4431.2    0.05       0  4982.5    0.03       0  4997.1    0.05       0
Bank Sta=4982.5,4997.1
Exp/Cntr=0.3,0.1