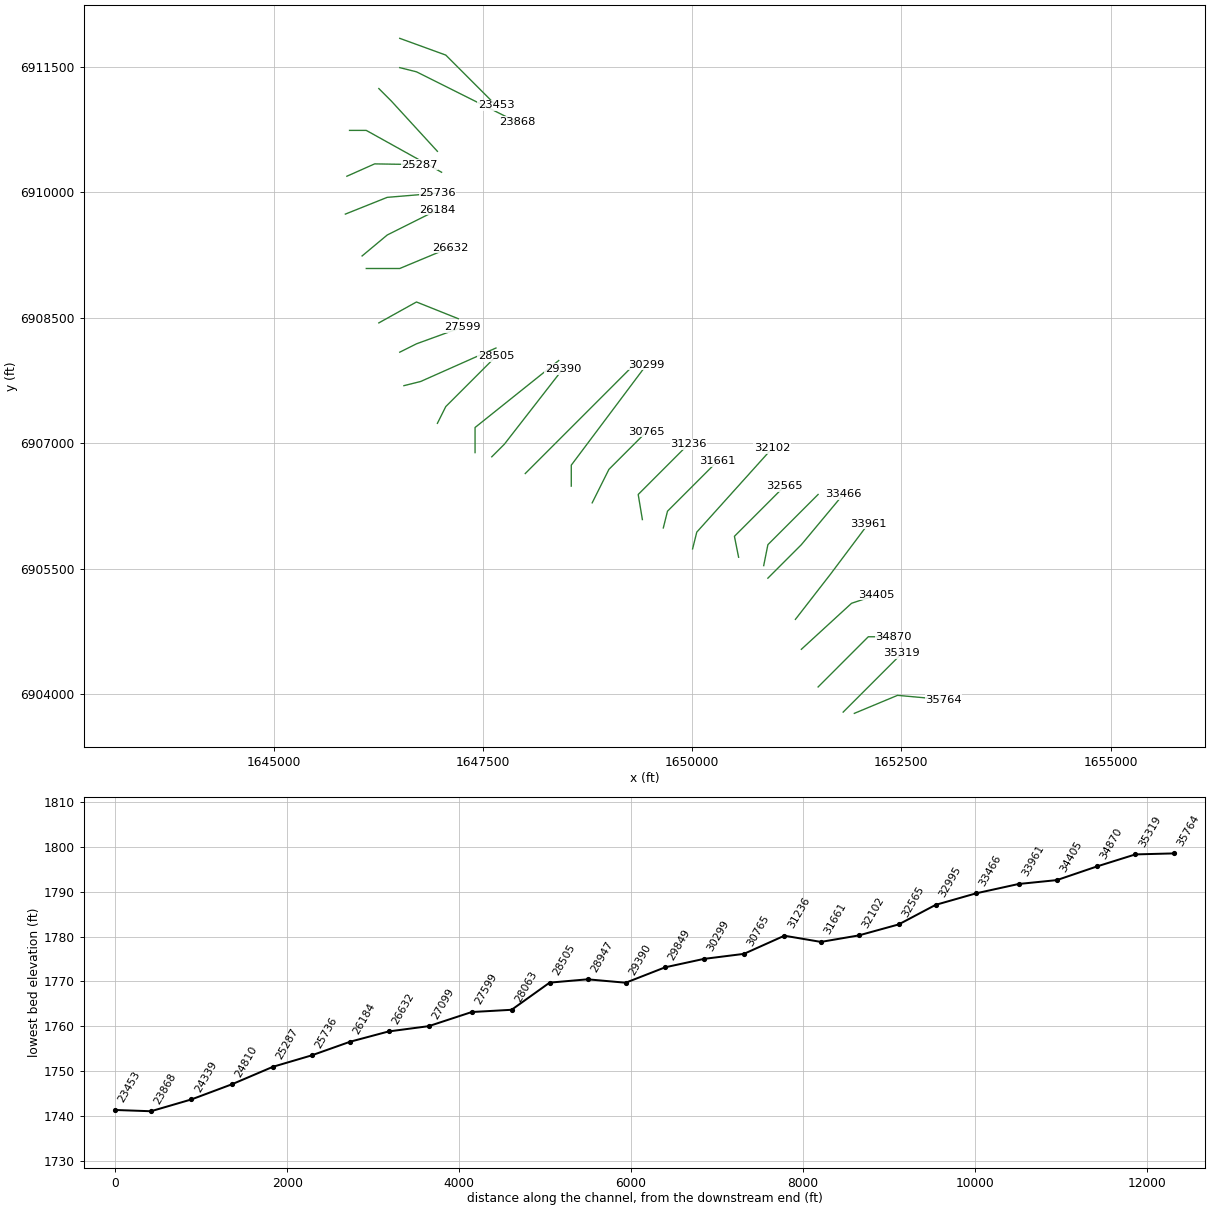
HEC-RAS study South Prong Long Creek.prj: South Prong Long Creek Base Level Engineering

--- South Prong Long Creek.g01 (geometry) --- (continued)

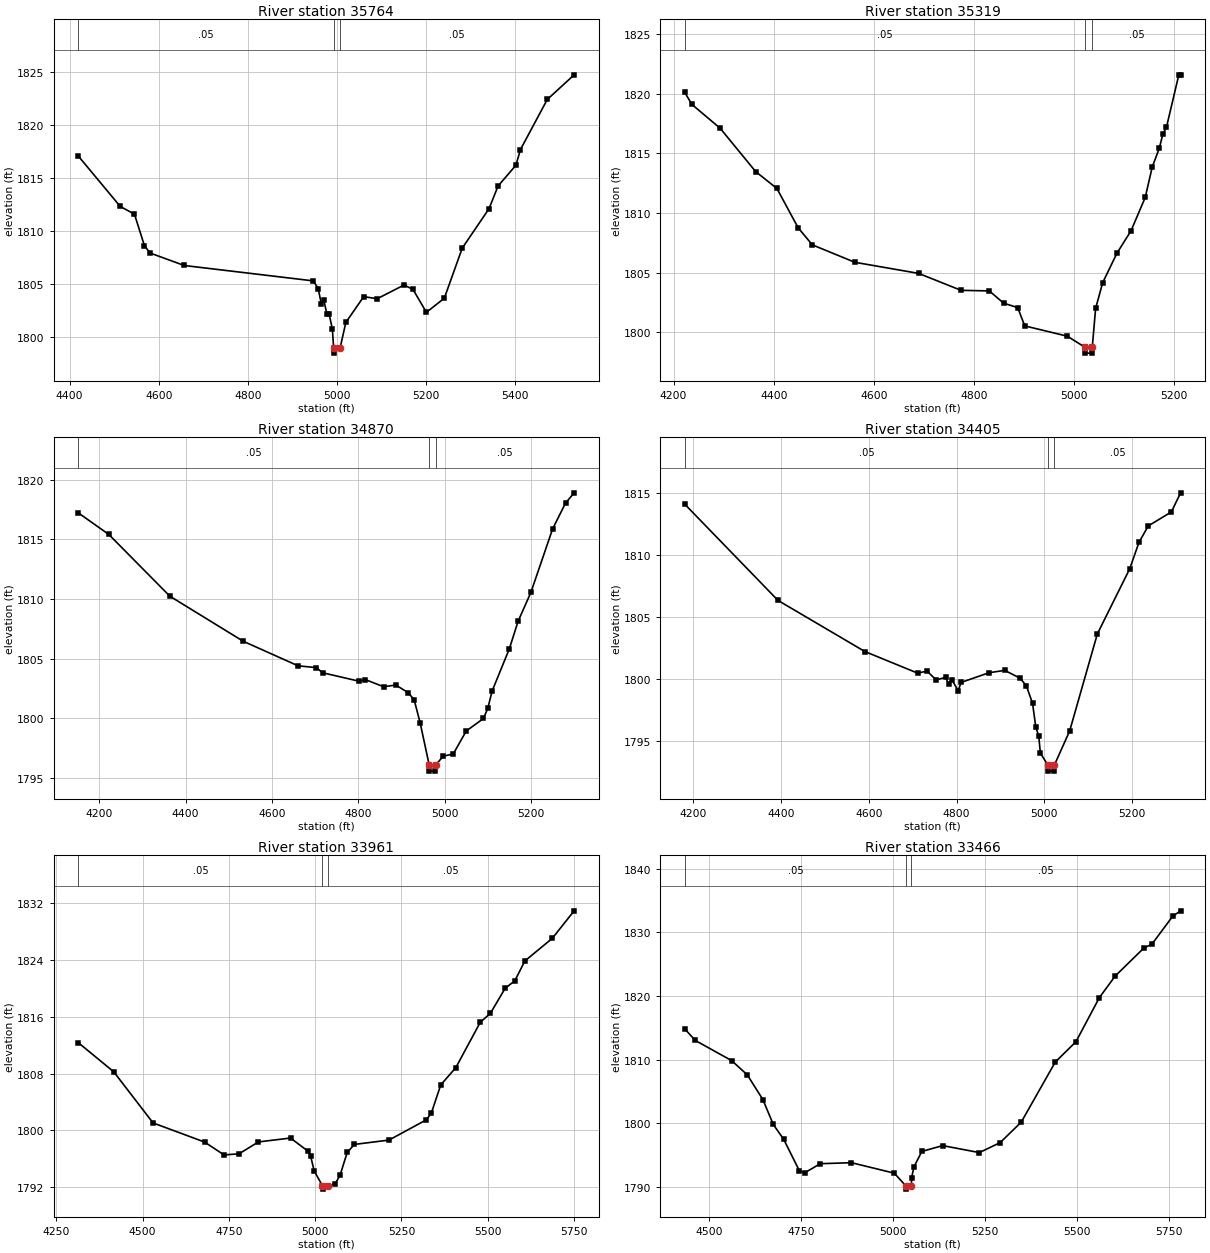
Type RM Length L Ch R = 1,35764,445,445,445
BEGIN DESCRIPTION:
South Prong Long Creek 71.0
END DESCRIPTION:
XS GIS Cut Line= 3
      1651938.27      6903772.70      1652455.00      6903988.00
      1653005.04      6903938.00
#Sta/Elev= 30
  4419.7 1817.04  4513.7 1812.30  4545.6 1811.57  4567.8 1808.62  4580.3 1807.92
  4657.2 1806.74  4947.0 1805.29  4957.8 1804.55  4964.9 1803.08  4970.3 1803.49
  4976.8 1802.22  4982.0 1802.22  4989.5 1800.74  4992.3 1798.99  4992.8 1798.49
  5006.9 1798.99  5019.7 1801.38  5059.8 1803.81  5089.9 1803.61  5150.2 1804.90
  5170.3 1804.49  5200.4 1802.33  5240.6 1803.66  5280.7 1808.37  5341.0 1812.10
  5361.1 1814.22  5401.2 1816.18  5411.3 1817.65  5471.5 1822.37  5531.8 1824.69
#Mann=3,-1,0
  4419.7    0.05       0  4992.3    0.03       0  5006.9    0.05       0
Bank Sta=4992.3,5006.9
Exp/Cntr=0.3,0.1

Type RM Length L Ch R = 1,35319,449,449,449
BEGIN DESCRIPTION:
South Prong Long Creek 70.0
END DESCRIPTION:
XS GIS Cut Line= 3
      1651804.99      6903787.99      1652355.00      6904338.00
      1652505.02      6904488.02
#Sta/Elev= 30
  4222.5 1820.10  4236.7 1819.10  4293.2 1817.10  4363.9 1813.48  4406.4 1812.06
  4448.8 1808.77  4477.1 1807.34  4561.9 1805.88  4689.2 1804.95  4774.1 1803.53
  4830.6 1803.48  4858.9 1802.46  4887.2 1802.08  4901.3 1800.55  4986.2 1799.69
  5021.2 1798.77  5021.7 1798.27  5035.6 1798.27  5036.1 1798.77  5042.8 1802.02
  5056.9 1804.17  5085.2 1806.63  5113.5 1808.52  5141.8 1811.31  5155.9 1813.87
  5170.0 1815.44  5177.1 1816.63  5184.2 1817.19  5208.9 1821.58  5212.5 1821.58
#Mann=3,-1,0
  4222.5    0.05       0  5021.2    0.05       0  5036.1    0.05       0
Bank Sta=5021.2,5036.1
Exp/Cntr=0.3,0.1

Type RM Length L Ch R = 1,34870,465,465,465
BEGIN DESCRIPTION:
South Prong Long Creek 69.0
END DESCRIPTION:
XS GIS Cut Line= 3
      1651505.03      6904088.03      1652105.00      6904688.00
      1652405.01      6904688.00
#Sta/Elev= 30
  4151.6 1817.21  4222.3 1815.40  4363.7 1810.23  4533.4 1806.46  4660.7 1804.40
  4703.1 1804.25  4717.2 1803.82  4802.1 1803.11  4816.2 1803.25  4858.7 1802.65
  4887.0 1802.79  4915.2 1802.16  4929.4 1801.57  4943.5 1799.60  4964.4 1796.08
  4964.9 1795.58  4978.8 1795.58  4979.3 1796.08  4996.6 1796.83  5020.1 1797.02
  5050.1 1798.94  5090.1 1799.99  5100.1 1800.85  5110.1 1802.29  5150.1 1805.84
  5170.1 1808.12  5200.1 1810.57  5250.1 1815.86  5280.1 1818.03  5300.1 1818.89
#Mann=3,-1,0
  4151.6    0.05       0  4964.4    0.05       0  4979.3    0.05       0
Bank Sta=4964.4,4979.3
Exp/Cntr=0.3,0.1

Type RM Length L Ch R = 1,34405,444,444,444
BEGIN DESCRIPTION:
South Prong Long Creek 68.0
END DESCRIPTION:
XS GIS Cut Line= 3
      1651305.00      6904538.00      1651905.00      6905088.00
      1652205.03      6905188.01
#Sta/Elev= 30
  4180.5 1814.06  4392.9 1806.31  4590.9 1802.19  4711.1 1800.45  4732.7 1800.61
  4753.6 1799.90  4775.2 1800.11  4782.0 1799.54  4789.4 1799.91  4803.6 1799.03
  4810.4 1799.70  4873.9 1800.48  4909.7 1800.67  4944.8 1800.04  4959.0 1799.43
  4973.2 1798.01  4980.6 1796.09  4987.3 1795.38  4991.0 1794.00  5008.0 1793.05
  5008.5 1792.55  5022.6 1792.55  5023.1 1793.05  5057.7 1795.78  5120.9 1803.61
  5194.7 1808.86  5215.8 1810.99  5236.9 1812.31  5289.6 1813.44  5310.7 1814.98
#Mann=3,-1,0
  4180.5    0.05       0  5008.0    0.05       0  5023.1    0.05       0
Bank Sta=5008,5023.1
Exp/Cntr=0.3,0.1

Type RM Length L Ch R = 1,33961,495,495,495
BEGIN DESCRIPTION:
South Prong Long Creek 67.0
END DESCRIPTION:
XS GIS Cut Line= 3
      1651234.10      6904896.02      1651655.00      6905438.00
      1652104.99      6906037.98
#Sta/Elev= 30
  4314.1 1812.35  4416.6 1808.25  4530.6 1801.03  4679.9 1798.33  4736.0 1796.52
  4779.5 1796.67  4835.7 1798.35  4928.8 1798.90  4978.6 1797.07  4986.8 1796.39
  4997.2 1794.26  5020.9 1792.19  5021.4 1791.69  5036.0 1792.19  5057.6 1792.40
  5072.2 1793.65  5093.0 1796.88  5113.9 1798.00  5213.9 1798.61  5322.2 1801.47
  5336.8 1802.45  5363.9 1806.40  5407.6 1808.84  5478.4 1815.24  5507.6 1816.49
  5550.3 1820.02  5578.4 1821.09  5607.6 1823.89  5686.8 1827.07  5750.3 1830.96
#Mann=3,-1,0
  4314.1    0.05       0  5020.9    0.05       0  5036.0    0.05       0
Bank Sta=5020.9,5036
Exp/Cntr=0.3,0.1

Type RM Length L Ch R = 1,33466,471,471,471
BEGIN DESCRIPTION:
South Prong Long Creek 66.0
END DESCRIPTION:
XS GIS Cut Line= 3
      1650904.99      6905387.99      1651305.00      6905788.00
      1651804.99      6906387.98
#Sta/Elev= 30
  4433.8 1814.82  4462.1 1813.01  4561.1 1809.83  4603.5 1807.59  4645.9 1803.70
  4674.2 1799.78  4702.5 1797.44  4744.9 1792.51  4759.1 1792.16  4801.5 1793.61
  4886.4 1793.77  5002.8 1792.12  5034.3 1790.11  5034.8 1789.61  5049.4 1790.11
  5049.6 1791.34  5056.1 1793.10  5077.6 1795.54  5134.2 1796.46  5233.8 1795.36
  5290.4 1796.93  5347.7 1800.16  5440.1 1809.61  5496.1 1812.80  5559.9 1819.75
  5602.8 1823.14  5680.9 1827.56  5702.4 1828.14  5759.0 1832.55  5780.5 1833.40
#Mann=3,-1,0
  4433.8    0.05       0  5034.3    0.03       0  5049.4    0.05       0
Bank Sta=5034.3,5049.4
Exp/Cntr=0.3,0.1

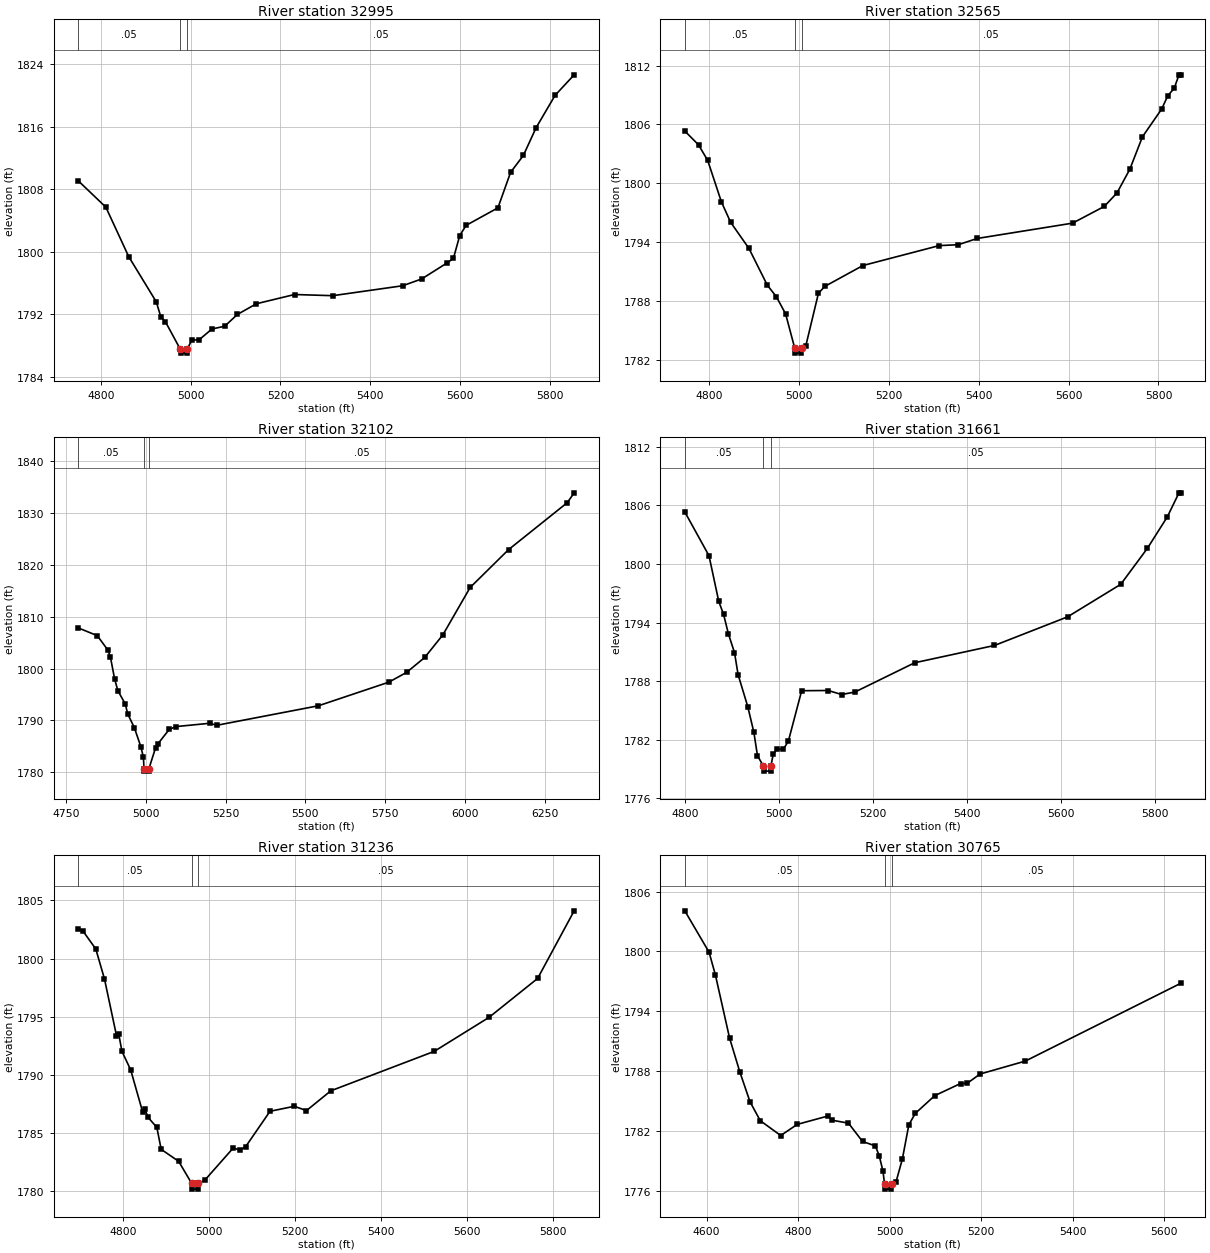
Type RM Length L Ch R = 1,32995,430,430,430
BEGIN DESCRIPTION:
South Prong Long Creek 65.0
END DESCRIPTION:
XS GIS Cut Line= 3
      1650855.00      6905537.98      1650905.00      6905788.00
      1651505.00      6906388.00
#Sta/Elev= 30
  4750.2 1809.08  4811.4 1805.72  4862.4 1799.38  4923.6 1793.61  4933.8 1791.68
  4944.0 1791.06  4977.1 1787.54  4977.6 1787.04  4992.0 1787.04  4992.5 1787.54
  5002.6 1788.70  5019.3 1788.76  5047.6 1790.13  5075.9 1790.48  5104.2 1791.99
  5146.6 1793.36  5231.4 1794.54  5316.3 1794.39  5471.9 1795.66  5514.3 1796.53
  5570.9 1798.58  5585.0 1799.17  5599.1 1802.09  5613.3 1803.39  5684.0 1805.63
  5712.3 1810.18  5740.6 1812.33  5768.8 1815.86  5811.3 1820.03  5853.7 1822.65
#Mann=3,-1,0
  4750.2    0.05       0  4977.1    0.03       0  4992.5    0.05       0
Bank Sta=4977.1,4992.5
Exp/Cntr=0.3,0.1

Type RM Length L Ch R = 1,32565,463,463,463
BEGIN DESCRIPTION:
South Prong Long Creek 64.0
END DESCRIPTION:
XS GIS Cut Line= 3
      1650555.00      6905638.02      1650505.00      6905888.00
      1651105.03      6906488.03
#Sta/Elev= 30
  4745.8 1805.33  4776.4 1803.92  4796.8 1802.33  4827.4 1798.09  4847.8 1796.03
  4888.6 1793.36  4929.3 1789.63  4949.7 1788.43  4970.1 1786.70  4990.5 1783.19
  4991.0 1782.69  5005.4 1782.69  5005.9 1783.19  5014.9 1783.39  5043.2 1788.79
  5057.3 1789.49  5142.2 1791.62  5311.9 1793.65  5354.3 1793.74  5396.7 1794.38
  5608.8 1795.94  5679.6 1797.65  5707.8 1799.03  5736.1 1801.42  5764.4 1804.75
  5806.8 1807.55  5821.0 1808.94  5835.1 1809.70  5845.7 1811.06  5849.3 1811.06
#Mann=3,-1,0
  4745.8    0.05       0  4990.5    0.03       0  5005.9    0.05       0
Bank Sta=4990.5,5005.9
Exp/Cntr=0.3,0.1

Type RM Length L Ch R = 1,32102,441,441,441
BEGIN DESCRIPTION:
South Prong Long Creek 63.0
END DESCRIPTION:
XS GIS Cut Line= 3
      1650005.00      6905738.01      1650055.00      6905938.00
      1650954.99      6906937.99
#Sta/Elev= 30
  4789.4 1807.81  4848.7 1806.32  4882.2 1803.52  4889.9 1802.18  4902.8 1798.02
  4913.1 1795.73  4936.3 1793.17  4944.0 1791.25  4964.6 1788.62  4985.2 1784.92
  4993.0 1782.92  4994.9 1780.75  4995.4 1780.25  5009.9 1780.25  5010.4 1780.75
  5031.1 1784.74  5037.8 1785.45  5073.7 1788.27  5094.6 1788.82  5200.7 1789.46
  5222.4 1789.07  5540.8 1792.83  5760.5 1797.36  5816.6 1799.25  5873.4 1802.13
  5930.2 1806.49  6015.4 1815.59  6135.7 1822.88  6319.6 1831.93  6340.9 1833.81
#Mann=3,-1,0
  4789.4    0.05       0  4994.9    0.03       0  5010.4    0.05       0
Bank Sta=4994.9,5010.4
Exp/Cntr=0.3,0.1

Type RM Length L Ch R = 1,31661,425,425,425
BEGIN DESCRIPTION:
South Prong Long Creek 62.0
END DESCRIPTION:
XS GIS Cut Line= 3
      1649655.00      6905987.99      1649705.00      6906188.00
      1650305.01      6906788.01
#Sta/Elev= 30
  4798.9 1805.33  4850.4 1800.84  4871.1 1796.17  4881.4 1794.84  4891.7 1792.84
  4904.6 1790.93  4912.3 1788.67  4932.9 1785.39  4945.8 1782.78  4953.5 1780.38
  4966.3 1779.30  4966.8 1778.80  4981.4 1778.80  4981.9 1779.30  4987.0 1780.53
  4994.8 1781.02  5008.6 1781.04  5019.2 1781.87  5047.5 1787.03  5104.1 1787.05
  5132.3 1786.64  5160.6 1786.89  5287.9 1789.89  5457.6 1791.66  5613.2 1794.59
  5726.3 1797.92  5782.9 1801.60  5825.3 1804.82  5850.1 1807.28  5853.6 1807.28
#Mann=3,-1,0
  4798.9    0.05       0  4966.3    0.03       0  4981.9    0.05       0
Bank Sta=4966.3,4981.9
Exp/Cntr=0.3,0.1

Type RM Length L Ch R = 1,31236,471,471,471
BEGIN DESCRIPTION:
South Prong Long Creek 61.0
END DESCRIPTION:
XS GIS Cut Line= 3
      1649405.00      6906087.98      1649355.00      6906388.00
      1649955.01      6906988.01
#Sta/Elev= 30
  4695.8 1802.55  4706.0 1802.39  4736.4 1800.82  4756.6 1798.24  4784.5 1793.38
  4789.6 1793.54  4797.2 1792.02  4817.5 1790.43  4845.4 1786.80  4850.4 1787.06
  4858.0 1786.34  4878.3 1785.49  4888.4 1783.60  4929.0 1782.57  4959.2 1780.68
  4959.7 1780.18  4974.3 1780.18  4974.8 1780.68  4989.8 1780.95  5056.5 1783.74
  5070.7 1783.52  5084.8 1783.83  5141.4 1786.87  5197.9 1787.30  5226.2 1786.93
  5282.8 1788.63  5523.2 1792.02  5650.5 1794.94  5763.6 1798.29  5848.5 1804.10
#Mann=3,-1,0
  4695.8    0.05       0  4959.2    0.03       0  4974.8    0.05       0
Bank Sta=4959.2,4974.8
Exp/Cntr=0.3,0.1

Type RM Length L Ch R = 1,30765,466,466,466
BEGIN DESCRIPTION:
South Prong Long Creek 60.0
END DESCRIPTION:
XS GIS Cut Line= 3
      1648805.01      6906288.03      1649005.00      6906688.00
      1649455.02      6907138.02
#Sta/Elev= 30
  4552.2 1804.07  4605.3 1799.91  4619.2 1797.61  4650.0 1791.31  4672.4 1787.91
  4694.7 1784.91  4717.1 1783.01  4761.8 1781.52  4798.1 1782.64  4865.2 1783.48
  4873.6 1783.06  4909.9 1782.76  4940.7 1780.92  4968.6 1780.48  4977.0 1779.50
  4985.4 1777.93  4988.7 1776.64  4989.2 1776.14  5003.9 1776.14  5004.4 1776.64
  5013.5 1776.81  5027.7 1779.16  5041.8 1782.59  5055.9 1783.74  5098.4 1785.52
  5154.9 1786.74  5169.1 1786.75  5197.4 1787.69  5296.4 1788.99  5635.8 1796.79
#Mann=3,-1,0
  4552.2    0.05       0  4988.7    0.03       0  5004.4    0.05       0
Bank Sta=4988.7,5004.4
Exp/Cntr=0.3,0.1

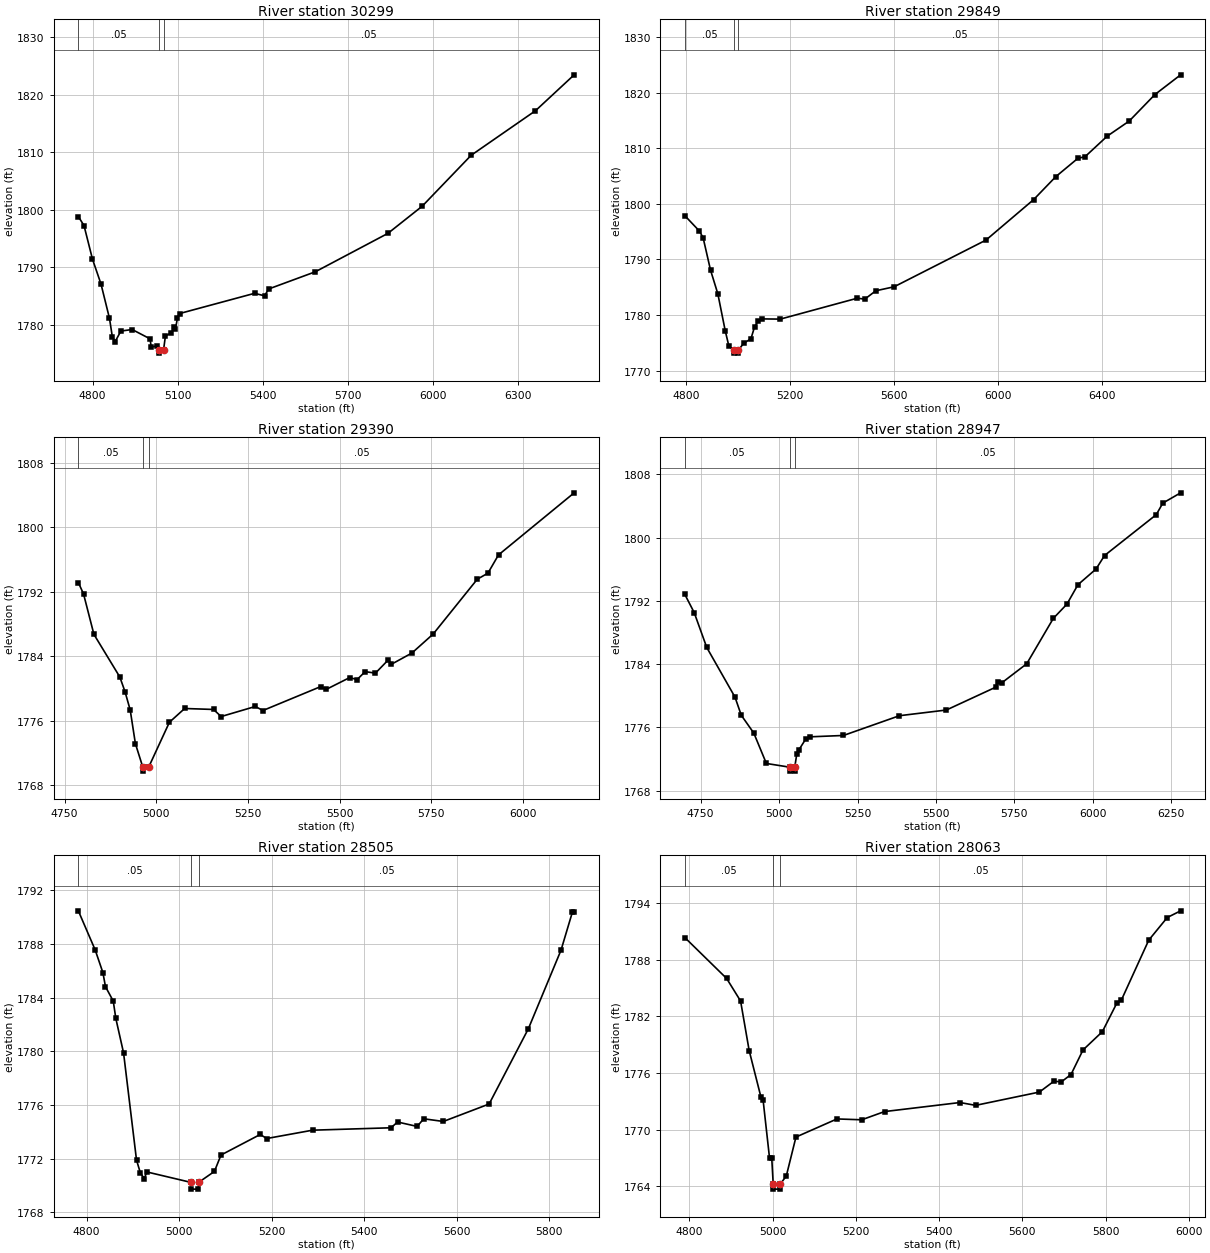
Type RM Length L Ch R = 1,30299,450,450,450
BEGIN DESCRIPTION:
South Prong Long Creek 59.0
END DESCRIPTION:
XS GIS Cut Line= 3
      1648555.00      6906488.01      1648555.00      6906738.00
      1649455.01      6907938.01
#Sta/Elev= 30
  4749.5 1798.80  4769.5 1797.23  4799.5 1791.37  4829.5 1787.05  4859.5 1781.06
  4869.5 1777.86  4879.5 1777.02  4899.5 1778.86  4939.5 1779.13  5002.6 1777.51
  5006.8 1776.06  5027.6 1776.31  5034.3 1775.52  5034.8 1775.02  5050.1 1775.52
  5056.8 1777.97  5077.6 1778.59  5085.9 1779.63  5092.2 1779.23  5099.5 1781.16
  5106.8 1781.91  5371.4 1785.43  5406.8 1785.00  5421.4 1786.19  5585.9 1789.18
  5842.2 1795.87  5963.0 1800.59  6135.9 1809.46  6363.0 1817.22  6499.5 1823.47
#Mann=3,-1,0
  4749.5    0.05       0  5034.3    0.03       0  5050.1    0.05       0
Bank Sta=5034.3,5050.1
Exp/Cntr=0.3,0.1

Type RM Length L Ch R = 1,29849,459,459,459
BEGIN DESCRIPTION:
South Prong Long Creek 58.0
END DESCRIPTION:
XS GIS Cut Line= 3
      1648004.98      6906637.98      1648155.00      6906788.00
      1649354.99      6907987.99
#Sta/Elev= 30
  4794.3 1797.89  4850.9 1795.10  4865.0 1793.88  4893.3 1788.10  4921.6 1783.81
  4949.9 1777.19  4964.0 1774.42  4984.3 1773.65  4984.8 1773.15  4999.8 1773.15
  5000.3 1773.65  5020.6 1774.91  5048.9 1775.73  5063.0 1777.88  5077.2 1778.94
  5091.3 1779.31  5162.0 1779.27  5459.0 1783.04  5487.3 1782.86  5529.7 1784.37
  5600.4 1785.09  5954.0 1793.49  6137.8 1800.79  6222.7 1804.90  6307.5 1808.19
  6335.8 1808.51  6420.7 1812.19  6505.5 1814.91  6604.5 1819.68  6703.5 1823.23
#Mann=3,-1,0
  4794.3    0.05       0  4984.3    0.05       0  5000.3    0.05       0
Bank Sta=4984.3,5000.3
Exp/Cntr=0.3,0.1

Type RM Length L Ch R = 1,29390,443,443,443
BEGIN DESCRIPTION:
South Prong Long Creek 57.0
END DESCRIPTION:
XS GIS Cut Line= 3
      1647604.97      6906837.97      1647755.00      6906988.00
      1648454.97      6907887.96
#Sta/Elev= 30
  4787.7 1793.15  4801.9 1791.73  4830.2 1786.71  4900.9 1781.41  4915.0 1779.59
  4929.2 1777.31  4943.3 1773.14  4963.5 1770.22  4964.0 1769.72  4979.6 1770.22
  5036.1 1775.79  5077.7 1777.50  5156.4 1777.38  5177.2 1776.50  5270.4 1777.75
  5291.2 1777.25  5448.7 1780.22  5463.2 1779.86  5527.4 1781.33  5548.2 1781.10
  5570.0 1782.08  5598.0 1781.89  5633.3 1783.55  5641.4 1782.99  5697.5 1784.39
  5755.5 1786.75  5875.8 1793.56  5904.8 1794.31  5933.7 1796.58  6140.0 1804.29
#Mann=3,-1,0
  4787.7    0.05       0  4963.5    0.05       0  4979.6    0.05       0
Bank Sta=4963.5,4979.6
Exp/Cntr=0.3,0.1

Type RM Length L Ch R = 1,28947,442,442,442
BEGIN DESCRIPTION:
South Prong Long Creek 56.0
END DESCRIPTION:
XS GIS Cut Line= 3
      1647405.00      6906887.98      1647405.00      6907188.00
      1648404.97      6907987.97
#Sta/Elev= 30
  4699.4 1792.84  4729.4 1790.53  4769.4 1786.12  4859.4 1779.84  4879.4 1777.55
  4919.4 1775.29  4959.4 1771.45  5033.7 1770.98  5034.2 1770.48  5049.4 1770.48
  5049.9 1770.98  5056.2 1772.60  5063.4 1773.19  5085.1 1774.55  5099.5 1774.82
  5205.1 1774.99  5383.6 1777.49  5533.3 1778.21  5690.2 1781.09  5696.6 1781.74
  5711.0 1781.68  5789.4 1784.06  5874.2 1789.80  5917.5 1791.60  5952.7 1794.06
  6010.3 1796.04  6037.5 1797.75  6202.4 1802.92  6223.2 1804.38  6280.0 1805.68
#Mann=3,-1,0
  4699.4    0.05       0  5033.7    0.03       0  5049.9    0.05       0
Bank Sta=5033.7,5049.9
Exp/Cntr=0.3,0.1

Type RM Length L Ch R = 1,28505,442,442,442
BEGIN DESCRIPTION:
South Prong Long Creek 55.0
END DESCRIPTION:
XS GIS Cut Line= 3
      1646954.99      6907237.98      1647055.00      6907438.00
      1647655.03      6908038.03
#Sta/Elev= 30
  4782.2 1790.47  4818.6 1787.56  4835.3 1785.87  4840.9 1784.82  4857.7 1783.75
  4863.3 1782.45  4880.0 1779.89  4908.0 1771.91  4916.4 1770.94  4924.8 1770.53
  4930.4 1771.02  5026.0 1770.24  5026.5 1769.74  5041.8 1769.74  5042.3 1770.24
  5076.5 1771.06  5090.7 1772.28  5175.5 1773.81  5189.7 1773.51  5288.7 1774.13
  5458.4 1774.31  5472.5 1774.74  5514.9 1774.41  5529.1 1774.98  5571.5 1774.78
  5670.5 1776.08  5755.4 1781.69  5826.1 1787.55  5850.8 1790.40  5854.4 1790.40
#Mann=3,-1,0
  4782.2    0.05       0  5026.0    0.03       0  5042.3    0.05       0
Bank Sta=5026,5042.3
Exp/Cntr=0.3,0.1

Type RM Length L Ch R = 1,28063,464,464,464
BEGIN DESCRIPTION:
South Prong Long Creek 54.0
END DESCRIPTION:
XS GIS Cut Line= 3
      1646554.99      6907688.00      1646755.00      6907738.00
      1647654.96      6908137.98
#Sta/Elev= 30
  4789.0 1790.37  4889.5 1786.03  4923.0 1783.64  4943.6 1778.39  4972.0 1773.44
  4977.1 1773.13  4992.6 1766.97  4997.9 1766.97  5001.4 1764.20  5001.9 1763.70
  5017.2 1763.70  5017.7 1764.20  5032.8 1765.09  5056.0 1769.22  5154.5 1771.14
  5214.0 1771.05  5268.7 1771.92  5450.0 1772.88  5487.6 1772.58  5640.8 1773.99
  5675.7 1775.14  5693.5 1775.07  5716.7 1775.85  5745.5 1778.45  5792.0 1780.39
  5826.8 1783.42  5837.8 1783.75  5903.4 1790.09  5947.9 1792.49  5980.0 1793.20
#Mann=3,-1,0
  4789.0    0.05       0  5001.4    0.05       0  5017.7    0.05       0
Bank Sta=5001.4,5017.7
Exp/Cntr=0.3,0.1

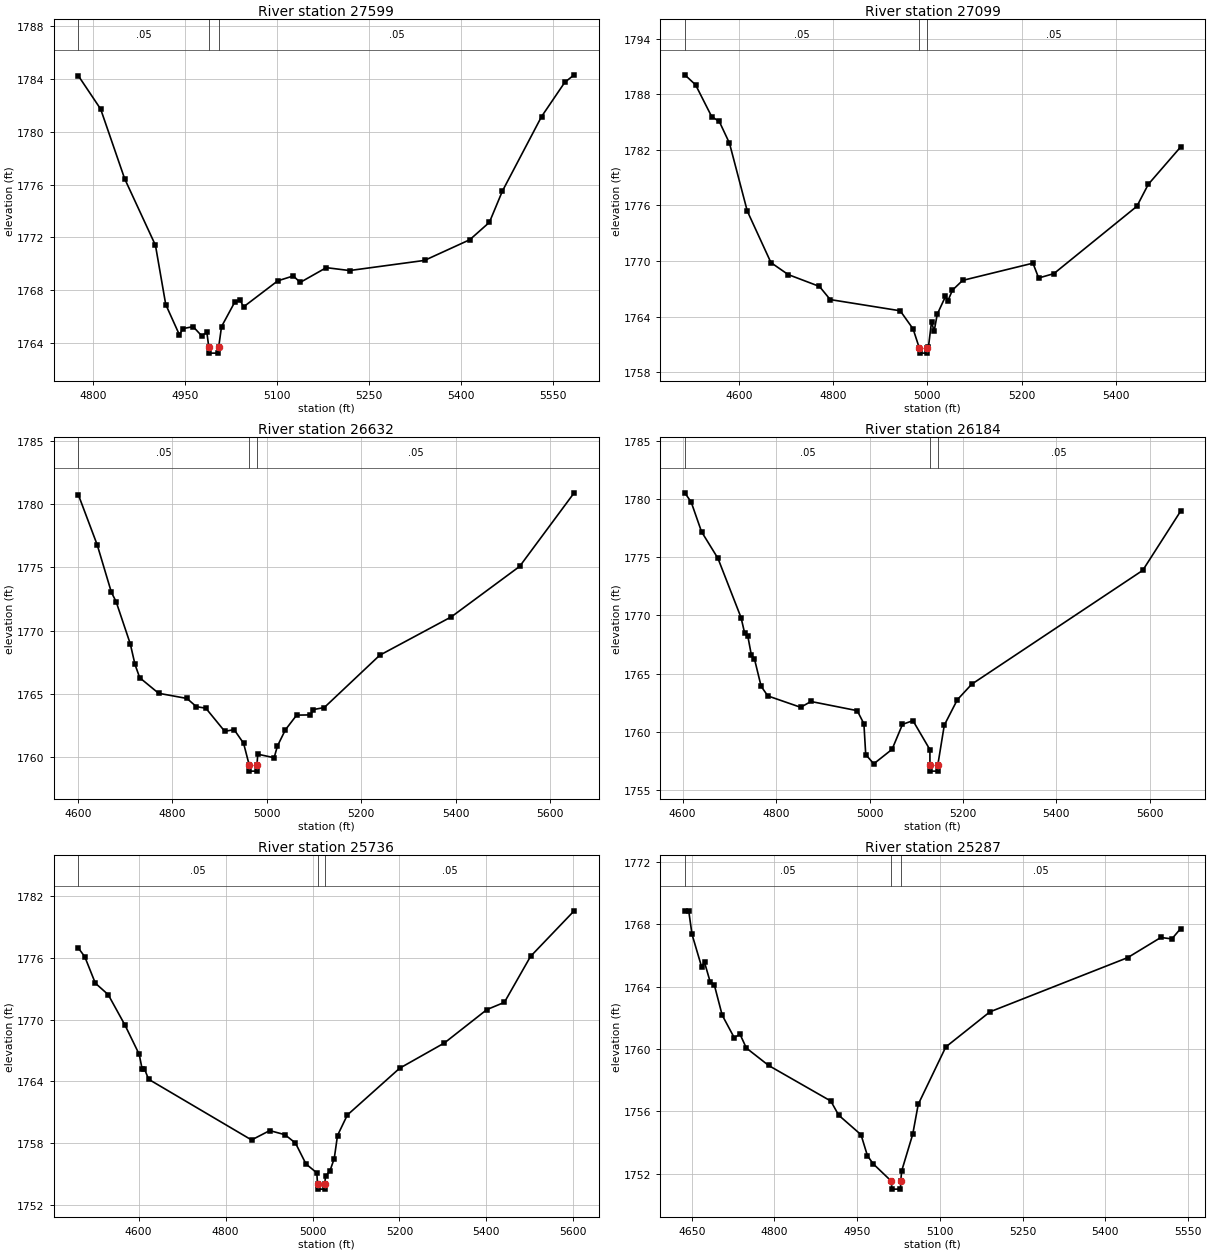
Type RM Length L Ch R = 1,27599,500,500,500
BEGIN DESCRIPTION:
South Prong Long Creek 53.0
END DESCRIPTION:
XS GIS Cut Line= 3
      1646504.96      6908087.98      1646705.00      6908188.00
      1647255.01      6908388.00
#Sta/Elev= 30
  4775.8 1784.26  4812.2 1781.73  4851.3 1776.45  4901.6 1771.39  4918.4 1766.89
  4940.8 1764.58  4946.3 1765.06  4963.1 1765.21  4977.1 1764.51  4985.5 1764.78
  4988.5 1763.70  4989.0 1763.20  5004.4 1763.20  5004.9 1763.70  5009.4 1765.21
  5031.4 1767.11  5040.0 1767.21  5045.3 1766.71  5101.2 1768.69  5126.5 1769.06
  5137.8 1768.57  5180.3 1769.69  5218.3 1769.47  5340.6 1770.24  5414.4 1771.81
  5446.4 1773.13  5467.6 1775.50  5531.5 1781.16  5569.4 1783.76  5584.7 1784.33
#Mann=3,-1,0
  4775.8    0.05       0  4988.5    0.03       0  5004.9    0.05       0
Bank Sta=4988.5,5004.9
Exp/Cntr=0.3,0.1

Type RM Length L Ch R = 1,27099,467,467,467
BEGIN DESCRIPTION:
South Prong Long Creek 52.0
END DESCRIPTION:
XS GIS Cut Line= 3
      1646255.01      6908438.00      1646705.00      6908688.00
      1647205.01      6908488.00
#Sta/Elev= 30
  4484.7 1790.10  4507.6 1789.02  4541.9 1785.58  4557.9 1785.07  4579.6 1782.72
  4617.4 1775.40  4667.7 1769.83  4704.3 1768.54  4770.7 1767.26  4793.6 1765.84
  4942.3 1764.63  4969.7 1762.67  4983.2 1760.56  4983.7 1760.06  4999.2 1760.06
  4999.7 1760.56  5002.2 1760.69  5008.9 1763.47  5014.3 1762.40  5021.0 1764.26
  5038.5 1766.18  5043.9 1765.74  5053.3 1766.86  5074.9 1767.91  5224.3 1769.77
  5236.4 1768.17  5268.7 1768.64  5445.1 1775.91  5469.3 1778.28  5538.0 1782.31
#Mann=3,-1,0
  4484.7    0.05       0  4983.2    0.05       0  4999.7    0.05       0
Bank Sta=4983.2,4999.7
Exp/Cntr=0.3,0.1

Type RM Length L Ch R = 1,26632,448,448,448
BEGIN DESCRIPTION:
South Prong Long Creek 51.0
END DESCRIPTION:
XS GIS Cut Line= 3
      1646104.98      6909088.00      1646505.00      6909088.00
      1647104.99      6909337.99
#Sta/Elev= 30
  4600.8 1780.75  4640.8 1776.78  4670.8 1773.03  4680.8 1772.29  4710.8 1768.95
  4720.8 1767.32  4730.8 1766.27  4770.8 1765.04  4830.8 1764.63  4850.8 1763.98
  4870.8 1763.86  4910.8 1762.03  4930.8 1762.16  4950.8 1761.08  4962.5 1759.38
  4963.0 1758.88  4978.6 1758.88  4979.1 1759.38  4980.8 1760.22  5015.4 1759.94
  5022.5 1760.87  5039.3 1762.15  5063.1 1763.31  5092.4 1763.33  5098.3 1763.75
  5121.6 1763.91  5239.1 1768.05  5390.8 1771.09  5535.4 1775.08  5650.8 1780.90
#Mann=3,-1,0
  4600.8    0.05       0  4962.5    0.03       0  4979.1    0.05       0
Bank Sta=4962.5,4979.1
Exp/Cntr=0.3,0.1

Type RM Length L Ch R = 1,26184,448,448,448
BEGIN DESCRIPTION:
South Prong Long Creek 50.0
END DESCRIPTION:
XS GIS Cut Line= 3
      1646054.97      6909237.97      1646355.00      6909488.00
      1646955.02      6909788.01
#Sta/Elev= 30
  4604.6 1780.57  4618.3 1779.77  4640.4 1777.22  4675.6 1774.92  4725.0 1769.82
  4732.9 1768.45  4739.4 1768.24  4747.2 1766.57  4753.7 1766.26  4768.0 1763.90
  4782.3 1763.07  4852.6 1762.09  4874.7 1762.59  4973.7 1761.80  4988.0 1760.67
  4991.9 1758.02  5009.1 1757.22  5048.3 1758.47  5070.6 1760.62  5093.0 1760.94
  5129.3 1758.44  5129.4 1757.09  5129.9 1756.59  5145.6 1756.59  5146.1 1757.09
  5160.1 1760.55  5188.0 1762.74  5218.8 1764.08  5584.9 1773.89  5666.0 1778.99
#Mann=3,-1,0
  4604.6    0.05       0  5129.4    0.03       0  5146.1    0.05       0
Bank Sta=5129.4,5146.1
Exp/Cntr=0.3,0.1

Type RM Length L Ch R = 1,25736,449,449,449
BEGIN DESCRIPTION:
South Prong Long Creek 49.0
END DESCRIPTION:
XS GIS Cut Line= 3
      1645854.99      6909738.00      1646355.00      6909938.00
      1646954.99      6909988.00
#Sta/Elev= 30
  4461.2 1776.94  4476.0 1776.10  4500.3 1773.53  4529.9 1772.42  4568.9 1769.43
  4601.2 1766.63  4608.0 1765.20  4613.3 1765.22  4622.8 1764.21  4859.7 1758.32
  4901.5 1759.23  4936.5 1758.83  4960.7 1758.02  4984.9 1755.99  5009.8 1755.13
  5011.4 1754.05  5011.9 1753.55  5027.6 1753.55  5028.1 1754.05  5029.8 1754.79
  5039.9 1755.31  5049.9 1756.52  5057.4 1758.75  5080.0 1760.74  5200.4 1765.28
  5303.3 1767.73  5401.1 1770.97  5441.3 1771.67  5501.5 1776.13  5601.8 1780.55
#Mann=3,-1,0
  4461.2    0.05       0  5011.4    0.05       0  5028.1    0.05       0
Bank Sta=5011.4,5028.1
Exp/Cntr=0.3,0.1

Type RM Length L Ch R = 1,25287,477,477,477
BEGIN DESCRIPTION:
South Prong Long Creek 48.0
END DESCRIPTION:
XS GIS Cut Line= 3
      1645873.03      6910190.31      1646205.00      6910338.00
      1646740.88      6910329.31
#Sta/Elev= 30
  4637.4 1768.83  4644.5 1768.87  4650.5 1767.36  4667.8 1765.29  4673.2 1765.56
  4683.3 1764.33  4691.0 1764.11  4705.2 1762.18  4727.1 1760.73  4737.5 1760.96
  4749.0 1760.07  4789.5 1758.95  4902.2 1756.67  4916.6 1755.76  4957.0 1754.51
  4968.6 1753.17  4978.9 1752.65  5012.3 1751.52  5012.8 1751.02  5028.6 1751.02
  5029.1 1751.52  5030.7 1752.18  5050.8 1754.54  5060.8 1756.46  5110.8 1760.14
  5190.8 1762.39  5440.8 1765.87  5500.8 1767.16  5520.8 1767.07  5536.7 1767.73
#Mann=3,-1,0
  4637.4    0.05       0  5012.3    0.03       0  5029.1    0.05       0
Bank Sta=5012.3,5029.1
Exp/Cntr=0.3,0.1

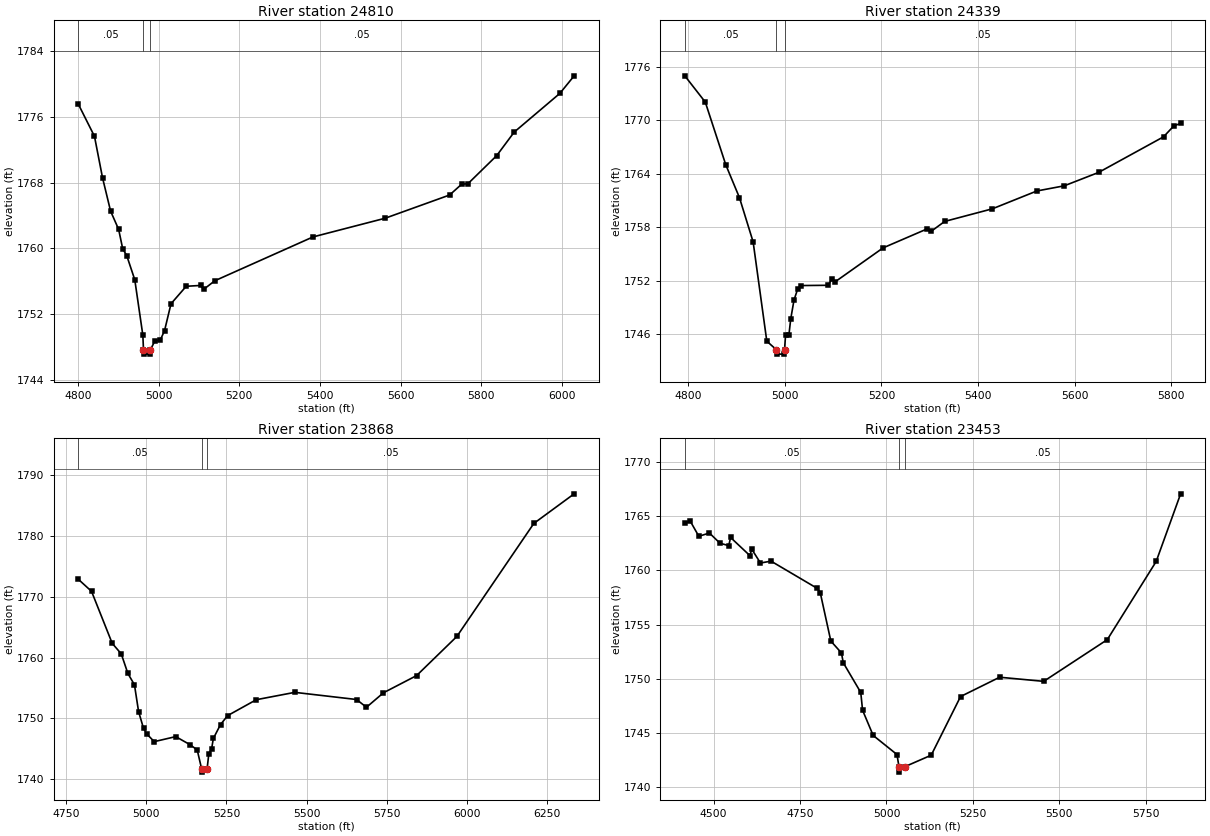
Type RM Length L Ch R = 1,24810,471,471,471
BEGIN DESCRIPTION:
South Prong Long Creek 47.0
END DESCRIPTION:
XS GIS Cut Line= 3
      1645904.98      6910738.00      1646105.00      6910738.00
      1647005.01      6910237.99
#Sta/Elev= 30
  4800.9 1777.56  4840.9 1773.65  4860.9 1768.60  4880.9 1764.54  4900.9 1762.31
  4910.9 1759.96  4920.9 1759.13  4940.9 1756.18  4960.9 1749.43  4962.5 1747.63
  4963.0 1747.13  4978.8 1747.13  4979.3 1747.63  4990.9 1748.75  5003.8 1748.81
  5014.7 1749.99  5030.7 1753.26  5068.4 1755.39  5103.9 1755.49  5111.9 1755.02
  5139.3 1756.06  5383.0 1761.40  5561.5 1763.67  5721.6 1766.50  5751.4 1767.81
  5767.4 1767.89  5838.3 1771.29  5881.8 1774.16  5995.0 1778.87  6030.5 1781.01
#Mann=3,-1,0
  4800.9    0.05       0  4962.5    0.05       0  4979.3    0.05       0
Bank Sta=4962.5,4979.3
Exp/Cntr=0.3,0.1

Type RM Length L Ch R = 1,24339,471,471,471
BEGIN DESCRIPTION:
South Prong Long Creek 46.0
END DESCRIPTION:
XS GIS Cut Line= 3
      1646255.03      6911237.97      1646405.00      6911088.00
      1646954.98      6910488.03
#Sta/Elev= 30
  4793.2 1775.01  4835.6 1772.06  4878.0 1765.02  4906.3 1761.33  4934.6 1756.36
  4962.9 1745.21  4982.7 1744.26  4983.2 1743.76  4999.1 1743.76  4999.6 1744.26
  5001.8 1745.95  5008.7 1745.95  5012.4 1747.71  5019.2 1749.84  5026.6 1751.04
  5033.4 1751.46  5090.1 1751.49  5097.5 1752.21  5104.3 1751.88  5203.5 1755.69
  5295.4 1757.84  5302.8 1757.54  5330.9 1758.66  5429.8 1760.08  5521.7 1762.08
  5578.4 1762.66  5649.4 1764.16  5783.8 1768.16  5805.4 1769.40  5819.2 1769.66
#Mann=3,-1,0
  4793.2    0.05       0  4982.7    0.03       0  4999.6    0.05       0
Bank Sta=4982.7,4999.6
Exp/Cntr=0.3,0.1

Type RM Length L Ch R = 1,23868,415,415,415
BEGIN DESCRIPTION:
South Prong Long Creek 45.0
END DESCRIPTION:
XS GIS Cut Line= 3
      1646504.98      6911488.00      1646705.00      6911438.00
      1647904.99      6910838.01
#Sta/Elev= 30
  4787.6 1772.89  4828.8 1770.91  4893.3 1762.35  4921.6 1760.61  4942.2 1757.39
  4962.8 1755.51  4975.7 1751.10  4991.2 1748.32  5002.2 1747.37  5024.5 1746.15
  5091.6 1746.98  5136.3 1745.65  5158.7 1744.79  5172.6 1741.63  5173.1 1741.13
  5189.5 1741.63  5195.0 1744.19  5203.4 1744.87  5209.0 1746.67  5231.4 1748.96
  5253.7 1750.44  5343.2 1753.06  5463.3 1754.27  5656.2 1753.09  5687.0 1751.81
  5740.1 1754.20  5843.5 1757.03  5969.3 1763.48  6209.6 1782.10  6335.4 1786.97
#Mann=3,-1,0
  4787.6    0.05       0  5172.6    0.05       0  5189.5    0.05       0
Bank Sta=5172.6,5189.5
Exp/Cntr=0.3,0.1

Type RM Length L Ch R = 1,23453,354,354,354
BEGIN DESCRIPTION:
South Prong Long Creek 44.0
END DESCRIPTION:
XS GIS Cut Line= 3
      1646504.96      6911838.01      1647055.00      6911638.00
      1647655.00      6911038.00
#Sta/Elev= 30
  4416.9 1764.31  4432.2 1764.55  4457.5 1763.13  4488.1 1763.43  4518.7 1762.49
  4544.0 1762.27  4549.3 1763.02  4605.1 1761.35  4610.5 1761.94  4635.7 1760.67
  4666.3 1760.84  4800.0 1758.33  4808.7 1757.92  4839.2 1753.48  4869.8 1752.39
  4875.2 1751.48  4925.7 1748.75  4931.0 1747.11  4961.6 1744.79  5030.5 1743.03
  5036.2 1741.91  5036.7 1741.41  5053.1 1741.91  5129.5 1742.97  5214.3 1748.37
  5327.4 1750.15  5454.7 1749.77  5638.6 1753.61  5780.0 1760.81  5850.7 1767.04
#Mann=3,-1,0
  4416.9    0.05       0  5036.2    0.05       0  5053.1    0.05       0
Bank Sta=5036.2,5053.1
Exp/Cntr=0.3,0.1