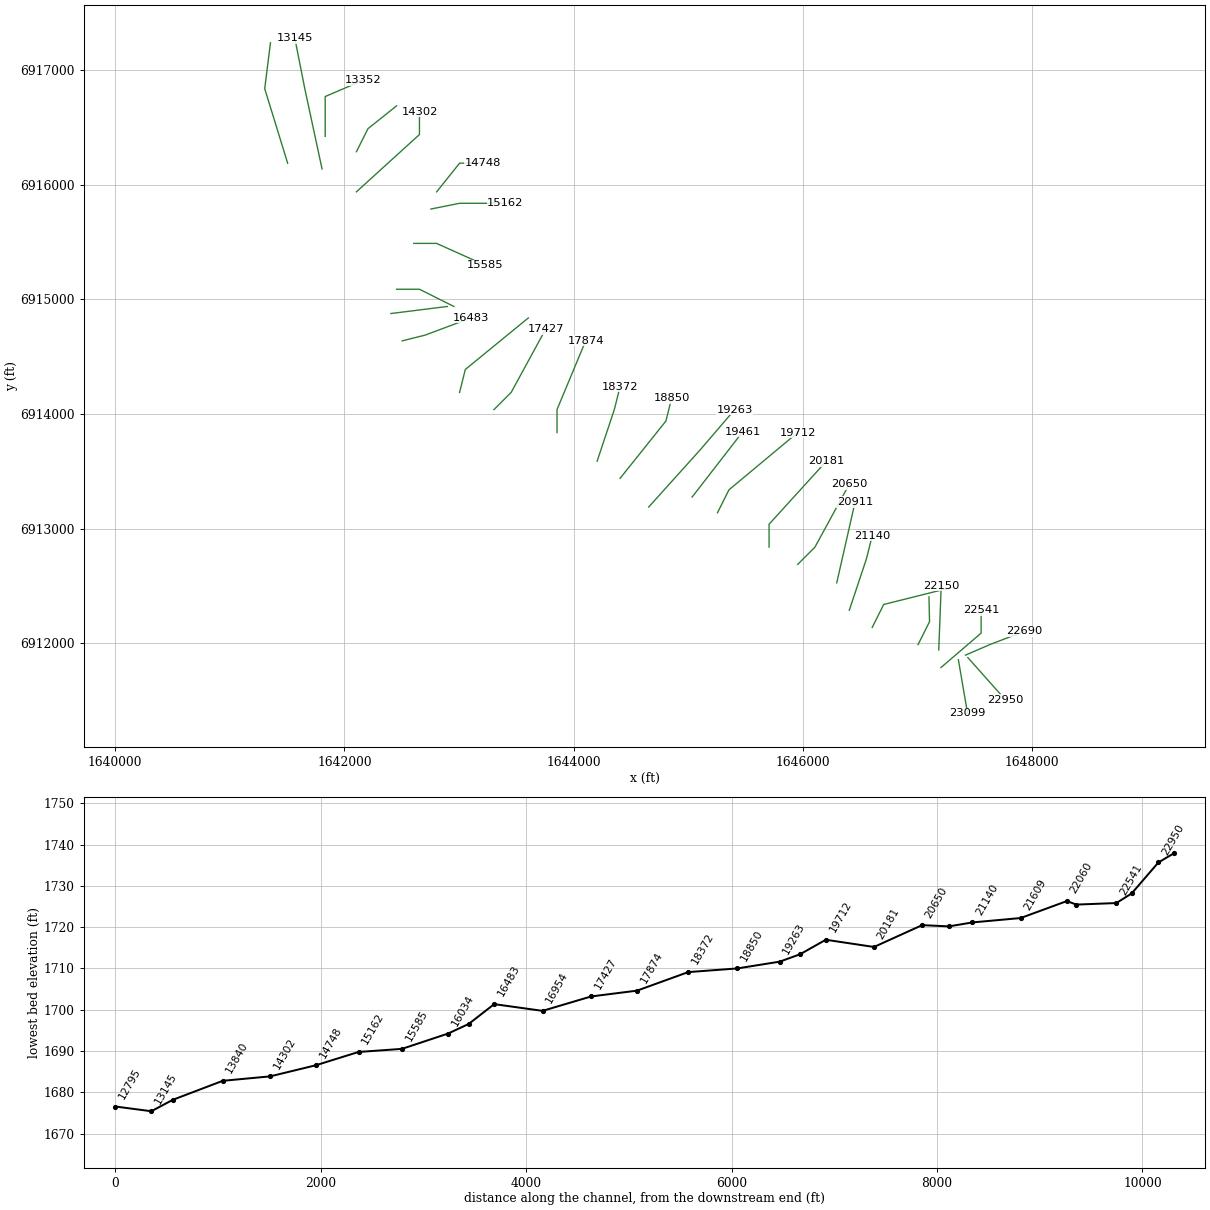
HEC-RAS study South Prong Long Creek.prj: South Prong Long Creek Base Level Engineering

--- South Prong Long Creek.g01 (geometry) --- (continued)

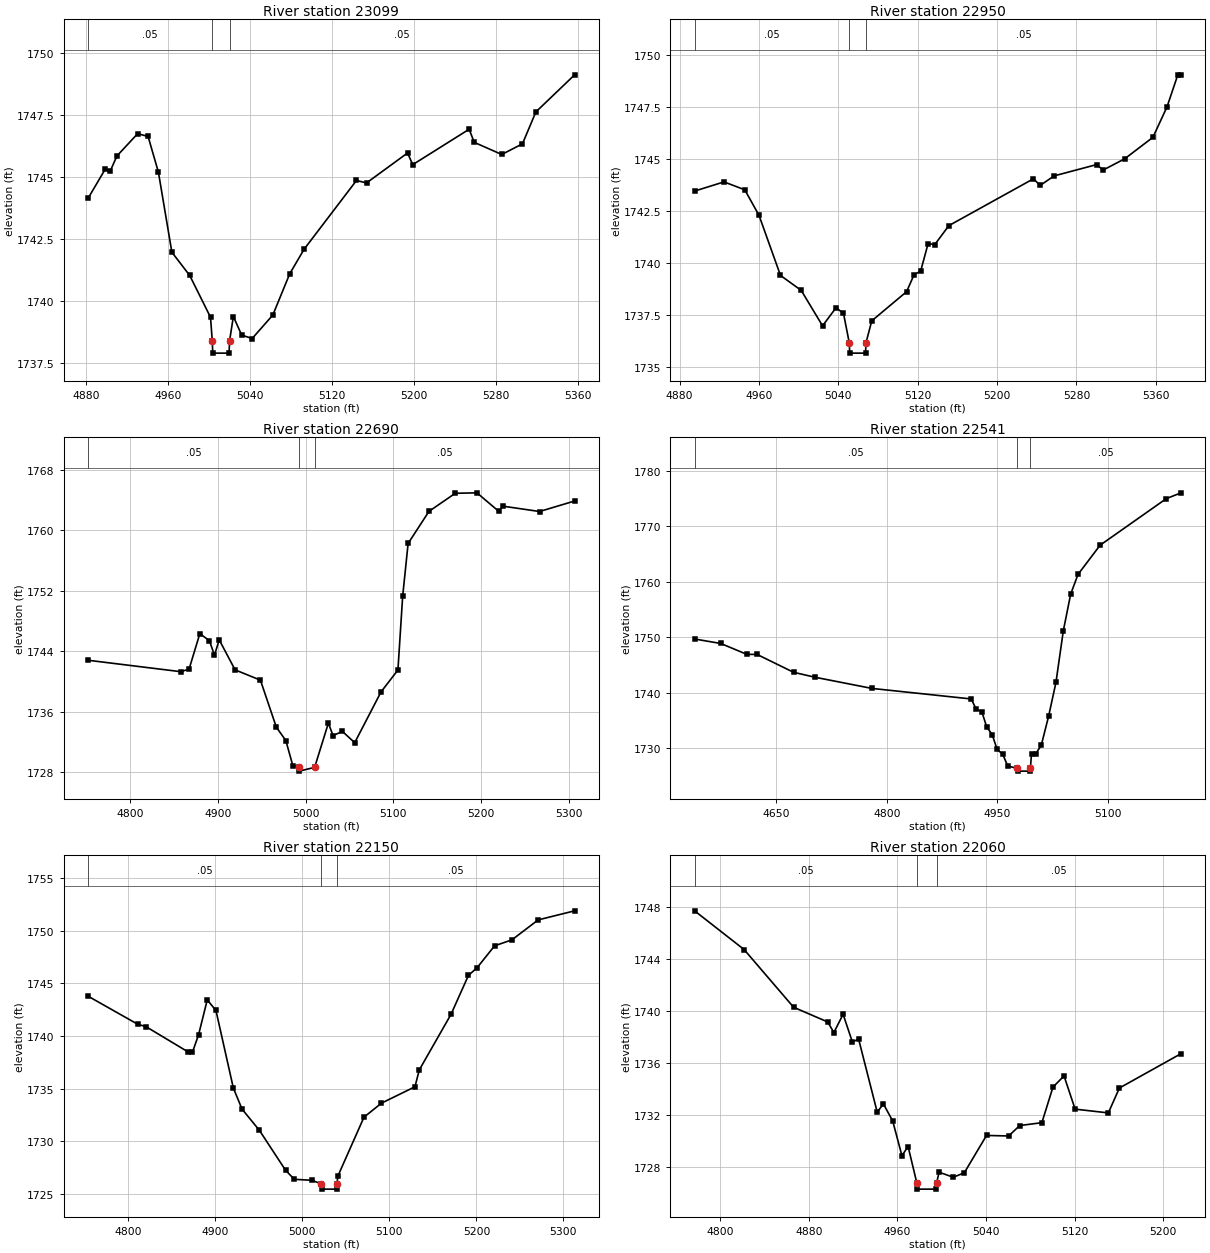
Type RM Length L Ch R = 1,23099,149,149,149
BEGIN DESCRIPTION:
Mapping XS 55679f51
END DESCRIPTION:
XS GIS Cut Line= 2
      1647356.57      6911855.65      1647436.76      6911387.88
#Sta/Elev= 30
  4882.2 1744.14  4898.8 1745.31  4903.8 1745.24  4910.3 1745.85  4930.5 1746.75
  4940.7 1746.64  4950.8 1745.19  4963.9 1741.96  4981.3 1741.02  5001.6 1739.33
  5003.3 1738.38  5003.8 1737.88  5019.7 1737.88  5020.2 1738.38  5023.9 1739.36
  5032.0 1738.61  5042.2 1738.47  5062.4 1739.42  5078.9 1741.09  5092.9 1742.08
  5144.0 1744.86  5153.8 1744.76  5193.8 1745.97  5198.9 1745.50  5253.9 1746.93
  5258.9 1746.40  5285.7 1745.91  5305.9 1746.34  5319.0 1747.63  5356.8 1749.13
#Mann=3,-1,0
  4882.2    0.05       0  5003.3    0.05       0  5020.2    0.05       0
Bank Sta=5003.3,5020.2
Exp/Cntr=0.3,0.1

Type RM Length L Ch R = 1,22950,260,260,260
BEGIN DESCRIPTION:
Mapping XS 64aba521
END DESCRIPTION:
XS GIS Cut Line= 2
      1647439.45      6911874.34      1647765.59      6911508.11
#Sta/Elev= 30
  4895.1 1743.46  4924.8 1743.90  4945.7 1743.52  4960.0 1742.30  4981.7 1739.41
  5002.6 1738.69  5024.1 1736.99  5037.7 1737.86  5045.2 1737.59  5051.0 1736.18
  5051.5 1735.68  5067.4 1735.68  5067.9 1736.18  5073.7 1737.23  5108.8 1738.63
  5116.3 1739.44  5123.0 1739.62  5130.5 1740.94  5137.2 1740.89  5151.4 1741.80
  5236.7 1744.05  5243.4 1743.73  5257.6 1744.19  5300.3 1744.73  5307.0 1744.47
  5328.7 1745.01  5357.1 1746.04  5371.3 1747.50  5382.2 1749.04  5385.5 1749.04
#Mann=3,-1,0
  4895.1    0.05       0  5051.0    0.05       0  5067.9    0.05       0
Bank Sta=5051,5067.9
Exp/Cntr=0.3,0.1

Type RM Length L Ch R = 1,22690,149,149,149
BEGIN DESCRIPTION:
Mapping XS eb2b8545
END DESCRIPTION:
XS GIS Cut Line= 3
      1647418.04      6911895.73      1647634.58      6911989.30
      1647932.30      6912103.60
#Sta/Elev= 30
  4752.1 1742.84  4857.7 1741.33  4867.2 1741.66  4879.5 1746.36  4890.4 1745.43
  4896.2 1743.51  4901.6 1745.54  4919.7 1741.57  4948.6 1740.21  4966.7 1734.00
  4977.6 1732.22  4985.5 1728.92  4992.4 1728.68  4992.9 1728.18  5010.4 1728.68
  5026.1 1734.53  5031.4 1732.87  5042.0 1733.44  5056.1 1731.94  5086.1 1738.65
  5105.4 1741.55  5110.8 1751.29  5117.0 1758.28  5140.8 1762.53  5170.8 1764.92
  5195.5 1764.98  5220.1 1762.56  5225.5 1763.21  5266.9 1762.51  5306.9 1763.90
#Mann=3,-1,0
  4752.1    0.05       0  4992.4    0.05       0  5010.4    0.05       0
Bank Sta=4992.4,5010.4
Exp/Cntr=0.3,0.1

Type RM Length L Ch R = 1,22541,391,391,391
BEGIN DESCRIPTION:
South Prong Long Creek 43.0
END DESCRIPTION:
XS GIS Cut Line= 3
      1647205.02      6911788.02      1647555.00      6912088.00
      1647555.00      6912287.95
#Sta/Elev= 30
  4539.0 1749.67  4574.6 1748.86  4609.8 1746.91  4624.0 1746.88  4673.4 1743.67
  4702.0 1742.79  4779.9 1740.76  4914.9 1738.86  4921.5 1737.01  4929.2 1736.57
  4935.7 1733.87  4943.4 1732.39  4950.0 1729.76  4957.7 1728.88  4964.3 1726.78
  4977.2 1726.35  4977.7 1725.85  4994.7 1725.85  4995.2 1726.35  4996.7 1728.99
  5002.4 1728.99  5009.9 1730.48  5019.9 1735.73  5029.9 1741.83  5039.9 1751.14
  5049.9 1757.76  5059.9 1761.32  5089.9 1766.58  5179.9 1774.98  5199.9 1776.02
#Mann=3,-1,0
  4539.0    0.05       0  4977.2    0.05       0  4995.2    0.05       0
Bank Sta=4977.2,4995.2
Exp/Cntr=0.3,0.1

Type RM Length L Ch R = 1,22150,90,90,90
BEGIN DESCRIPTION:
Mapping XS 32b4a81c
END DESCRIPTION:
XS GIS Cut Line= 2
      1647185.50      6911941.22      1647206.88      6912499.91
#Sta/Elev= 30
  4753.8 1743.78  4810.6 1741.13  4820.6 1740.88  4868.6 1738.50  4873.6 1738.45
  4880.7 1740.11  4890.7 1743.43  4900.7 1742.43  4920.7 1735.07  4930.7 1733.07
  4950.7 1731.05  4980.7 1727.27  4990.8 1726.41  5010.8 1726.32  5021.8 1725.98
  5022.3 1725.48  5039.3 1725.48  5039.8 1725.98  5040.8 1726.71  5070.8 1732.30
  5090.8 1733.63  5129.4 1735.19  5134.4 1736.79  5170.9 1742.07  5190.9 1745.76
  5200.9 1746.49  5220.9 1748.56  5240.9 1749.13  5271.0 1751.02  5312.9 1751.88
#Mann=3,-1,0
  4753.8    0.05       0  5021.8    0.05       0  5039.8    0.05       0
Bank Sta=5021.8,5039.8
Exp/Cntr=0.3,0.1

Type RM Length L Ch R = 1,22060,451,451,451
BEGIN DESCRIPTION:
South Prong Long Creek 42.0
END DESCRIPTION:
XS GIS Cut Line= 3
      1647005.01      6911988.02      1647105.00      6912188.00
      1647100.02      6912403.66
#Sta/Elev= 30
  4776.8 1747.70  4821.5 1744.73  4866.2 1740.30  4897.0 1739.17  4902.6 1738.36
  4910.9 1739.76  4919.3 1737.63  4924.9 1737.86  4941.7 1732.25  4947.3 1732.88
  4955.7 1731.57  4964.0 1728.91  4969.6 1729.61  4977.4 1726.84  4977.9 1726.34
  4994.9 1726.34  4995.4 1726.84  4997.6 1727.64  5010.4 1727.25  5020.4 1727.60
  5040.4 1730.46  5060.4 1730.42  5070.4 1731.22  5090.4 1731.44  5100.4 1734.17
  5110.4 1735.03  5120.4 1732.48  5150.4 1732.19  5160.4 1734.10  5216.1 1736.74
#Mann=3,-1,0
  4776.8    0.05       0  4977.4    0.05       0  4995.4    0.05       0
Bank Sta=4977.4,4995.4
Exp/Cntr=0.3,0.1

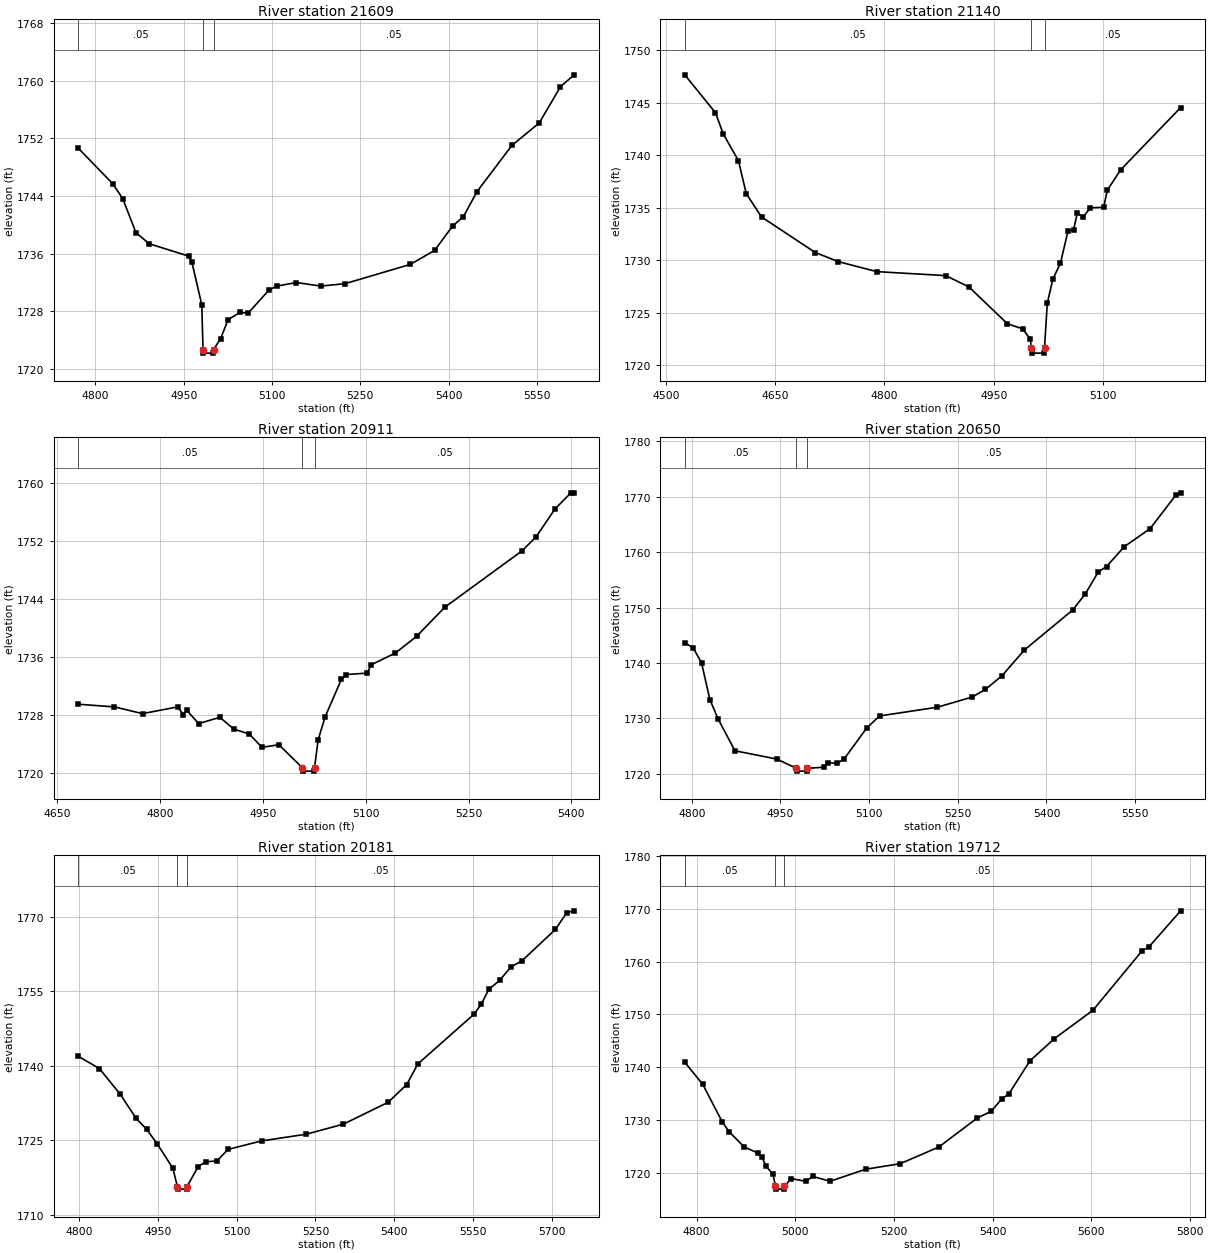
Type RM Length L Ch R = 1,21609,469,469,469
BEGIN DESCRIPTION:
South Prong Long Creek 41.0
END DESCRIPTION:
XS GIS Cut Line= 3
      1646604.99      6912137.99      1646705.00      6912338.00
      1647305.01      6912488.00
#Sta/Elev= 30
  4771.1 1750.62  4829.8 1745.68  4846.6 1743.62  4868.9 1738.93  4891.3 1737.39
  4958.4 1735.67  4964.0 1734.82  4980.7 1728.94  4982.9 1722.72  4983.4 1722.22
  5000.4 1722.22  5000.9 1722.72  5012.8 1724.24  5025.6 1726.88  5046.3 1727.88
  5059.1 1727.73  5095.2 1730.99  5108.1 1731.51  5141.6 1732.01  5182.8 1731.51
  5224.1 1731.85  5334.9 1734.52  5376.1 1736.45  5407.0 1739.86  5425.1 1741.14
  5448.3 1744.62  5507.5 1751.02  5553.9 1754.13  5590.0 1759.16  5613.2 1760.80
#Mann=3,-1,0
  4771.1    0.05       0  4982.9    0.03       0  5000.9    0.05       0
Bank Sta=4982.9,5000.9
Exp/Cntr=0.3,0.1

Type RM Length L Ch R = 1,21140,229,229,229
BEGIN DESCRIPTION:
South Prong Long Creek 40.0
END DESCRIPTION:
XS GIS Cut Line= 3
      1646405.01      6912288.04      1646555.00      6912738.00
      1646605.01      6912938.05
#Sta/Elev= 30
  4526.0 1747.66  4568.1 1744.05  4578.7 1742.05  4599.7 1739.47  4610.3 1736.35
  4631.4 1734.12  4705.1 1730.74  4736.8 1729.87  4789.5 1728.92  4884.3 1728.54
  4916.0 1727.46  4968.7 1723.96  4989.8 1723.47  5000.3 1722.48  5001.6 1721.66
  5002.1 1721.16  5019.2 1721.16  5019.7 1721.66  5023.5 1725.91  5031.2 1728.22
  5041.5 1729.71  5051.8 1732.75  5059.6 1732.93  5064.7 1734.49  5072.4 1734.11
  5082.8 1735.00  5100.8 1735.04  5105.9 1736.67  5124.0 1738.60  5206.5 1744.54
#Mann=3,-1,0
  4526.0    0.05       0  5001.6    0.05       0  5019.7    0.05       0
Bank Sta=5001.6,5019.7
Exp/Cntr=0.3,0.1

Type RM Length L Ch R = 1,20911,261,261,261
BEGIN DESCRIPTION:
Mapping XS 2700c016
END DESCRIPTION:
XS GIS Cut Line= 2
      1646295.35      6912526.62      1646455.74      6913232.32
#Sta/Elev= 30
  4680.5 1729.45  4733.2 1729.08  4774.2 1728.15  4825.5 1729.08  4833.7 1728.02
  4838.9 1728.59  4856.2 1726.77  4887.0 1727.64  4907.5 1726.01  4930.1 1725.33
  4948.5 1723.49  4973.2 1723.85  5007.2 1720.70  5007.7 1720.20  5024.8 1720.20
  5025.3 1720.70  5030.6 1724.56  5040.8 1727.72  5064.5 1732.91  5071.6 1733.56
  5102.4 1733.75  5107.5 1734.88  5143.4 1736.54  5174.2 1738.83  5215.2 1742.85
  5328.0 1750.65  5348.5 1752.58  5376.2 1756.44  5399.4 1758.68  5404.2 1758.68
#Mann=3,-1,0
  4680.5    0.05       0  5007.2    0.05       0  5025.3    0.05       0
Bank Sta=5007.2,5025.3
Exp/Cntr=0.3,0.1

Type RM Length L Ch R = 1,20650,469,469,469
BEGIN DESCRIPTION:
South Prong Long Creek 39.0
END DESCRIPTION:
XS GIS Cut Line= 3
      1645954.99      6912687.99      1646105.00      6912838.00
      1646404.98      6913387.96
#Sta/Elev= 30
  4788.3 1743.64  4802.5 1742.75  4816.6 1740.04  4830.7 1733.41  4844.9 1729.85
  4873.2 1724.17  4943.9 1722.68  4977.2 1721.00  4977.7 1720.50  4994.9 1720.50
  4995.4 1721.00  5023.2 1721.21  5030.3 1722.04  5046.0 1721.90  5057.9 1722.72
  5095.8 1728.25  5117.7 1730.46  5215.4 1732.03  5273.8 1733.85  5296.6 1735.23
  5324.6 1737.69  5362.6 1742.35  5444.2 1749.56  5466.0 1752.53  5487.9 1756.49
  5501.6 1757.42  5531.5 1761.00  5575.2 1764.25  5618.9 1770.32  5626.9 1770.72
#Mann=3,-1,0
  4788.3    0.05       0  4977.2    0.05       0  4995.4    0.05       0
Bank Sta=4977.2,4995.4
Exp/Cntr=0.3,0.1

Type RM Length L Ch R = 1,20181,469,469,469
BEGIN DESCRIPTION:
South Prong Long Creek 38.0
END DESCRIPTION:
XS GIS Cut Line= 3
      1645705.00      6912838.01      1645705.00      6913038.00
      1646205.01      6913588.01
#Sta/Elev= 30
  4798.8 1741.91  4838.8 1739.46  4878.8 1734.25  4908.8 1729.42  4928.8 1727.24
  4948.8 1724.32  4978.8 1719.38  4987.2 1715.71  4987.7 1715.21  5004.9 1715.21
  5005.4 1715.71  5026.8 1719.73  5041.0 1720.70  5062.6 1720.88  5083.6 1723.20
  5147.4 1724.90  5232.3 1726.25  5303.2 1728.28  5388.3 1732.68  5423.5 1736.23
  5444.8 1740.39  5551.2 1750.35  5565.4 1752.38  5579.6 1755.36  5600.5 1757.19
  5621.5 1759.86  5643.1 1761.15  5706.6 1767.45  5728.2 1770.82  5742.1 1771.17
#Mann=3,-1,0
  4798.8    0.05       0  4987.2    0.03       0  5005.4    0.05       0
Bank Sta=4987.2,5005.4
Exp/Cntr=0.3,0.1

Type RM Length L Ch R = 1,19712,251,251,251
BEGIN DESCRIPTION:
South Prong Long Creek 37.0
END DESCRIPTION:
XS GIS Cut Line= 3
      1645254.99      6913137.98      1645355.00      6913338.00
      1645955.04      6913838.03
#Sta/Elev= 30
  4776.2 1740.95  4812.6 1736.78  4851.7 1729.74  4865.7 1727.85  4896.4 1724.95
  4924.4 1723.78  4932.7 1722.97  4941.1 1721.26  4955.1 1719.74  4959.9 1717.46
  4960.4 1716.96  4977.7 1716.96  4978.2 1717.46  4991.4 1718.96  5021.3 1718.44
  5035.6 1719.35  5070.8 1718.45  5142.4 1720.72  5212.7 1721.77  5290.8 1724.92
  5368.9 1730.41  5397.5 1731.71  5418.3 1734.03  5432.6 1734.93  5475.6 1741.24
  5525.1 1745.42  5603.2 1750.79  5702.8 1762.03  5716.4 1762.75  5780.9 1769.60
#Mann=3,-1,0
  4776.2    0.05       0  4959.9    0.03       0  4978.2    0.05       0
Bank Sta=4959.9,4978.2
Exp/Cntr=0.3,0.1

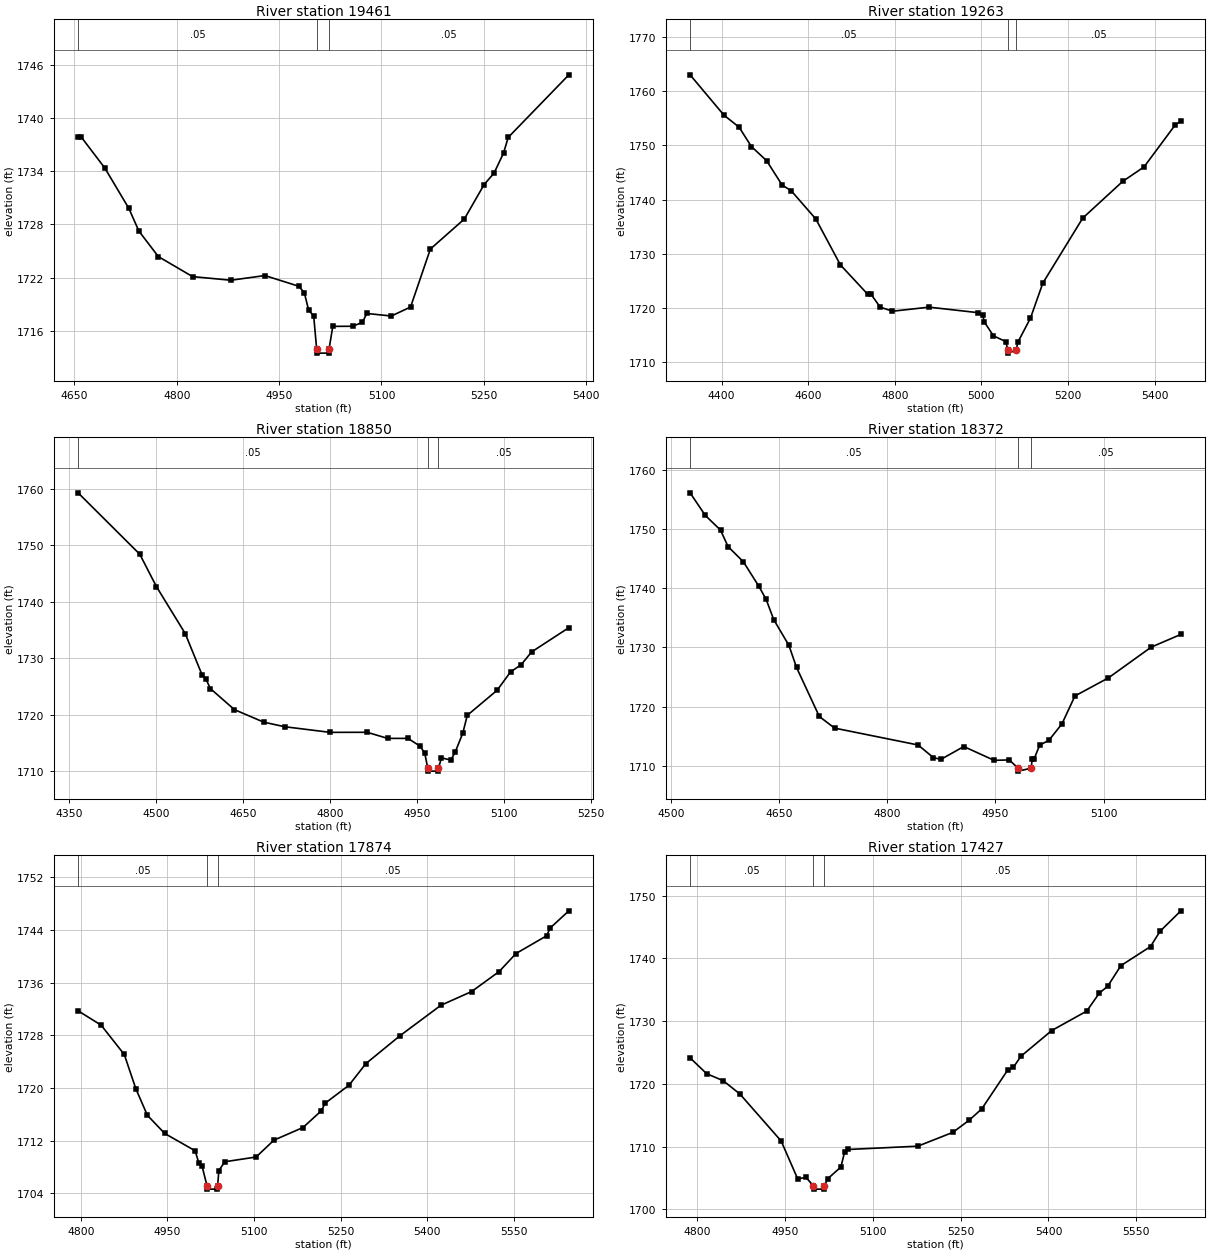
Type RM Length L Ch R = 1,19461,198,198,198
BEGIN DESCRIPTION:
Mapping XS 8e5675cc
END DESCRIPTION:
XS GIS Cut Line= 2
      1645033.63      6913275.06      1645474.13      6913843.70
#Sta/Elev= 30
  4655.4 1737.86  4660.4 1737.86  4694.6 1734.39  4729.9 1729.81  4744.4 1727.27
  4773.0 1724.37  4823.2 1722.10  4879.3 1721.69  4929.1 1722.22  4978.9 1721.01
  4987.0 1720.27  4993.4 1718.28  5000.7 1717.66  5005.0 1713.94  5005.5 1713.44
  5022.8 1713.44  5023.3 1713.94  5028.7 1716.47  5057.6 1716.48  5072.1 1716.92
  5078.5 1717.93  5114.5 1717.64  5142.7 1718.66  5171.7 1725.22  5221.5 1728.62
  5250.5 1732.52  5265.0 1733.81  5278.9 1736.08  5285.8 1737.86  5374.7 1744.94
#Mann=3,-1,0
  4655.4    0.05       0  5005.0    0.03       0  5023.3    0.05       0
Bank Sta=5005,5023.3
Exp/Cntr=0.3,0.1

Type RM Length L Ch R = 1,19263,413,413,413
BEGIN DESCRIPTION:
South Prong Long Creek 36.0
END DESCRIPTION:
XS GIS Cut Line= 3
      1644654.99      6913187.99      1645105.00      6913688.00
      1645405.02      6914038.02
#Sta/Elev= 30
  4327.0 1763.05  4405.1 1755.61  4440.2 1753.38  4468.6 1749.81  4503.8 1747.19
  4539.7 1742.68  4560.6 1741.64  4617.4 1736.43  4674.2 1727.95  4737.7 1722.49
  4744.4 1722.58  4766.1 1720.15  4794.5 1719.39  4879.0 1720.14  4992.6 1719.12
  5003.0 1718.61  5006.8 1717.39  5027.7 1714.85  5056.2 1713.78  5061.3 1712.15
  5061.8 1711.65  5079.6 1712.15  5084.8 1713.77  5113.3 1718.12  5141.8 1724.58
  5234.0 1736.59  5326.2 1743.36  5375.6 1746.04  5446.9 1753.72  5460.7 1754.52
#Mann=3,-1,0
  4327.0    0.05       0  5061.3    0.05       0  5079.6    0.05       0
Bank Sta=5061.3,5079.6
Exp/Cntr=0.3,0.1

Type RM Length L Ch R = 1,18850,478,478,478
BEGIN DESCRIPTION:
South Prong Long Creek 35.0
END DESCRIPTION:
XS GIS Cut Line= 3
      1644405.03      6913438.04      1644805.00      6913938.00
      1644855.00      6914137.98
#Sta/Elev= 30
  4365.8 1759.32  4472.2 1748.44  4501.0 1742.69  4550.6 1734.38  4579.5 1727.09
  4585.9 1726.41  4593.9 1724.64  4635.5 1720.90  4685.9 1718.69  4721.9 1717.88
  4800.4 1716.88  4864.4 1716.89  4899.6 1715.81  4934.8 1715.81  4955.6 1714.43
  4963.6 1713.21  4968.9 1710.51  4969.4 1710.01  4986.7 1710.01  4987.2 1710.51
  4992.5 1712.37  5008.6 1711.97  5016.4 1713.44  5029.3 1716.76  5037.0 1719.90
  5088.5 1724.34  5111.7 1727.60  5129.8 1728.85  5147.8 1731.12  5212.2 1735.43
#Mann=3,-1,0
  4365.8    0.05       0  4968.9    0.05       0  4987.2    0.05       0
Bank Sta=4968.9,4987.2
Exp/Cntr=0.3,0.1

Type RM Length L Ch R = 1,18372,498,498,498
BEGIN DESCRIPTION:
South Prong Long Creek 34.0
END DESCRIPTION:
XS GIS Cut Line= 3
      1644205.00      6913588.00      1644355.00      6914038.00
      1644405.00      6914238.00
#Sta/Elev= 30
  4526.7 1756.08  4547.8 1752.27  4568.9 1749.79  4579.4 1747.00  4600.5 1744.46
  4621.6 1740.40  4632.1 1738.12  4642.7 1734.68  4663.7 1730.35  4674.3 1726.61
  4705.9 1718.34  4727.0 1716.38  4842.9 1713.53  4864.0 1711.40  4874.6 1711.11
  4906.2 1713.27  4948.3 1710.94  4969.4 1711.01  4981.3 1709.62  4981.8 1709.12
  4999.7 1709.62  5001.0 1711.14  5003.6 1711.14  5011.4 1713.50  5024.2 1714.32
  5042.3 1717.09  5060.3 1721.80  5106.7 1724.85  5166.0 1730.04  5207.2 1732.19
#Mann=3,-1,0
  4526.7    0.05       0  4981.3    0.05       0  4999.7    0.05       0
Bank Sta=4981.3,4999.7
Exp/Cntr=0.3,0.1

Type RM Length L Ch R = 1,17874,447,447,447
BEGIN DESCRIPTION:
South Prong Long Creek 33.0
END DESCRIPTION:
XS GIS Cut Line= 3
      1643855.00      6913838.04      1643855.00      6914038.00
      1644105.02      6914638.04
#Sta/Elev= 30
  4795.2 1731.73  4835.2 1729.54  4875.2 1725.09  4895.2 1719.89  4915.2 1715.85
  4945.2 1713.09  4997.9 1710.46  5004.4 1708.58  5009.8 1708.17  5018.5 1705.13
  5019.0 1704.63  5036.4 1704.63  5036.9 1705.13  5039.0 1707.45  5049.3 1708.79
  5103.5 1709.51  5134.4 1712.07  5184.7 1713.99  5216.7 1716.55  5222.7 1717.66
  5264.4 1720.42  5293.6 1723.70  5352.7 1727.94  5423.6 1732.57  5476.7 1734.65
  5524.4 1737.69  5553.6 1740.43  5606.7 1743.13  5612.7 1744.30  5645.2 1746.92
#Mann=3,-1,0
  4795.2    0.05       0  5018.5    0.03       0  5036.9    0.05       0
Bank Sta=5018.5,5036.9
Exp/Cntr=0.3,0.1

Type RM Length L Ch R = 1,17427,473,473,473
BEGIN DESCRIPTION:
South Prong Long Creek 32.0
END DESCRIPTION:
XS GIS Cut Line= 3
      1643304.97      6914037.97      1643455.00      6914188.00
      1643755.01      6914738.02
#Sta/Elev= 30
  4787.6 1724.15  4815.9 1721.63  4844.2 1720.51  4872.5 1718.41  4943.2 1710.90
  4971.5 1704.85  4985.6 1705.10  4998.5 1703.72  4999.0 1703.22  5016.6 1703.22
  5017.1 1703.72  5022.6 1704.86  5045.3 1706.74  5051.5 1709.08  5057.2 1709.54
  5176.8 1710.07  5236.6 1712.27  5264.1 1714.18  5286.0 1716.01  5330.1 1722.17
  5340.1 1722.65  5352.9 1724.40  5405.6 1728.51  5465.4 1731.61  5487.2 1734.51
  5501.0 1735.54  5523.8 1738.86  5574.5 1741.91  5590.7 1744.34  5626.3 1747.60
#Mann=3,-1,0
  4787.6    0.05       0  4998.5    0.03       0  5017.1    0.05       0
Bank Sta=4998.5,5017.1
Exp/Cntr=0.3,0.1

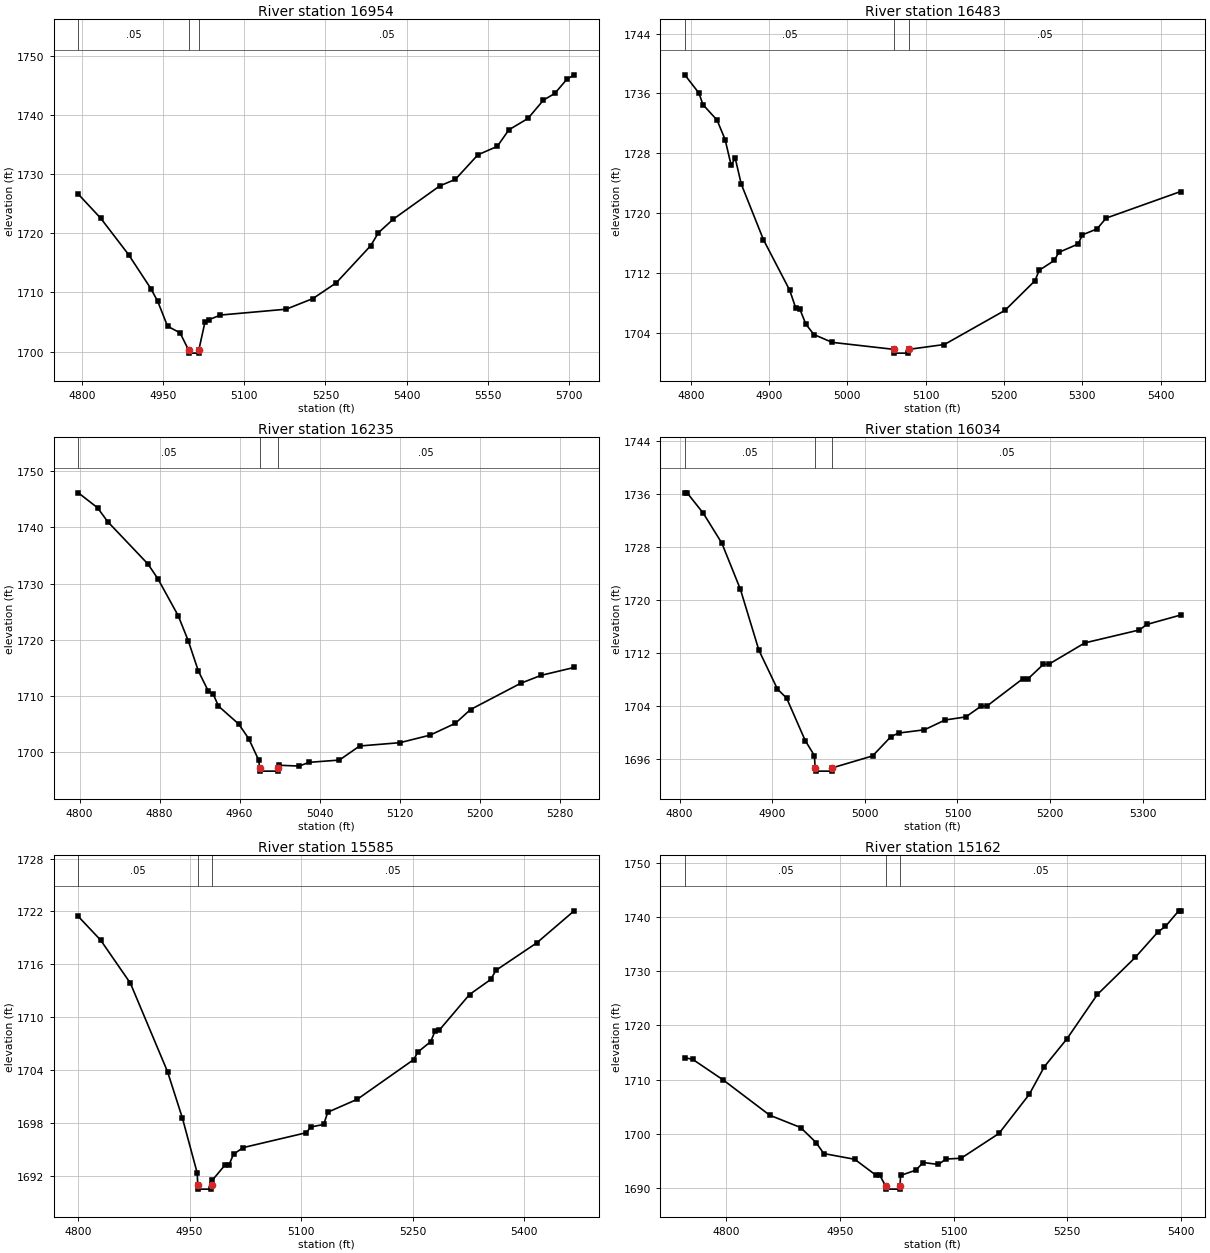
Type RM Length L Ch R = 1,16954,471,471,471
BEGIN DESCRIPTION:
South Prong Long Creek 31.0
END DESCRIPTION:
XS GIS Cut Line= 3
      1643005.00      6914188.01      1643055.00      6914388.00
      1643605.02      6914838.02
#Sta/Elev= 30
  4793.2 1726.65  4834.4 1722.60  4886.0 1716.43  4927.2 1710.67  4940.1 1708.48
  4958.1 1704.30  4981.3 1703.16  4997.2 1700.23  4997.7 1699.73  5015.4 1699.73
  5015.9 1700.23  5027.3 1704.96  5035.2 1705.41  5056.0 1706.18  5177.4 1707.17
  5226.9 1708.97  5270.0 1711.63  5333.8 1717.93  5348.2 1720.14  5375.5 1722.42
  5461.6 1728.06  5490.3 1729.16  5532.0 1733.32  5567.8 1734.75  5589.4 1737.56
  5624.6 1739.48  5653.3 1742.60  5674.1 1743.71  5696.3 1746.09  5710.0 1746.87
#Mann=3,-1,0
  4793.2    0.05       0  4997.2    0.05       0  5015.9    0.05       0
Bank Sta=4997.2,5015.9
Exp/Cntr=0.3,0.1

Type RM Length L Ch R = 1,16483,248,248,248
BEGIN DESCRIPTION:
South Prong Long Creek 30.0
END DESCRIPTION:
XS GIS Cut Line= 3
      1642505.04      6914638.01      1642705.00      6914688.00
      1643104.98      6914837.99
#Sta/Elev= 30
  4792.4 1738.49  4810.4 1736.06  4815.6 1734.51  4833.6 1732.45  4843.9 1729.85
  4851.6 1726.42  4856.8 1727.37  4864.5 1723.92  4892.9 1716.48  4926.4 1709.75
  4934.1 1707.38  4939.2 1707.27  4947.0 1705.23  4957.3 1703.84  4980.5 1702.80
  5059.5 1701.86  5060.0 1701.36  5077.7 1701.36  5078.2 1701.86  5124.0 1702.51
  5201.4 1707.07  5239.7 1711.02  5245.0 1712.41  5264.6 1713.74  5270.0 1714.80
  5294.9 1715.92  5300.2 1717.14  5318.9 1717.93  5330.5 1719.37  5425.7 1722.92
#Mann=3,-1,0
  4792.4    0.05       0  5059.5    0.05       0  5078.2    0.05       0
Bank Sta=5059.5,5078.2
Exp/Cntr=0.3,0.1

Type RM Length L Ch R = 1,16235,201,201,201
BEGIN DESCRIPTION:
Mapping XS 40ab45dc
END DESCRIPTION:
XS GIS Cut Line= 2
      1642405.97      6914876.26      1642897.84      6914937.75
#Sta/Elev= 30
  4798.8 1746.17  4818.0 1743.51  4828.1 1741.04  4868.4 1733.48  4878.4 1730.83
  4898.6 1724.28  4908.7 1719.79  4918.8 1714.41  4928.8 1710.80  4933.8 1710.23
  4938.9 1708.15  4959.1 1704.96  4969.1 1702.36  4979.2 1698.49  4980.0 1697.06
  4980.5 1696.56  4998.2 1696.56  4998.7 1697.06  4999.4 1697.61  5019.5 1697.46
  5029.6 1698.13  5059.8 1698.53  5080.0 1701.04  5120.3 1701.63  5150.5 1702.98
  5175.7 1705.08  5190.9 1707.54  5241.2 1712.23  5261.4 1713.63  5294.5 1715.04
#Mann=3,-1,0
  4798.8    0.05       0  4980.0    0.03       0  4998.7    0.05       0
Bank Sta=4980,4998.7
Exp/Cntr=0.3,0.1

Type RM Length L Ch R = 1,16034,449,449,449
BEGIN DESCRIPTION:
South Prong Long Creek 29.0
END DESCRIPTION:
XS GIS Cut Line= 3
      1642454.97      6915088.00      1642655.00      6915088.00
      1642954.97      6914938.02
#Sta/Elev= 30
  4805.6 1736.13  4808.1 1736.13  4825.6 1733.05  4845.6 1728.55  4865.6 1721.62
  4885.6 1712.44  4905.6 1706.59  4915.6 1705.21  4935.6 1698.84  4945.6 1696.55
  4946.3 1694.73  4946.8 1694.23  4964.5 1694.23  4965.0 1694.73  5008.4 1696.52
  5028.0 1699.40  5036.4 1699.96  5064.3 1700.45  5086.7 1701.93  5109.0 1702.39
  5125.8 1704.04  5131.4 1703.98  5170.5 1708.13  5176.1 1708.11  5192.9 1710.32
  5198.5 1710.31  5237.6 1713.54  5296.3 1715.48  5304.7 1716.32  5341.0 1717.73
#Mann=3,-1,0
  4805.6    0.05       0  4946.3    0.05       0  4965.0    0.05       0
Bank Sta=4946.3,4965
Exp/Cntr=0.3,0.1

Type RM Length L Ch R = 1,15585,423,423,423
BEGIN DESCRIPTION:
South Prong Long Creek 28.0
END DESCRIPTION:
XS GIS Cut Line= 3
      1642605.00      6915488.00      1642805.00      6915488.00
      1643230.99      6915296.38
#Sta/Elev= 30
  4800.4 1721.43  4830.4 1718.75  4870.4 1713.87  4920.4 1703.84  4940.4 1698.58
  4960.4 1692.33  4961.0 1691.02  4961.5 1690.52  4979.2 1690.52  4979.7 1691.02
  4980.4 1691.50  4997.9 1693.27  5003.1 1693.27  5009.2 1694.48  5022.3 1695.23
  5107.3 1696.92  5112.8 1697.56  5130.5 1697.85  5136.0 1699.24  5175.8 1700.71
  5251.7 1705.21  5257.2 1706.06  5274.5 1707.24  5280.4 1708.45  5285.9 1708.53
  5326.7 1712.58  5355.3 1714.29  5362.2 1715.32  5417.1 1718.43  5467.5 1722.07
#Mann=3,-1,0
  4800.4    0.05       0  4961.0    0.05       0  4979.7    0.05       0
Bank Sta=4961,4979.7
Exp/Cntr=0.3,0.1

Type RM Length L Ch R = 1,15162,414,414,414
BEGIN DESCRIPTION:
South Prong Long Creek 27.0
END DESCRIPTION:
XS GIS Cut Line= 3
      1642754.99      6915788.00      1643005.00      6915838.00
      1643405.04      6915838.00
#Sta/Elev= 30
  4745.0 1714.01  4755.2 1713.74  4796.0 1709.89  4857.2 1703.41  4898.0 1701.14
  4918.4 1698.37  4928.6 1696.33  4969.4 1695.28  4997.4 1692.35  5002.5 1692.35
  5010.6 1690.27  5011.1 1689.77  5028.8 1689.77  5029.3 1690.27  5030.0 1692.29
  5050.0 1693.26  5060.0 1694.68  5080.0 1694.32  5090.0 1695.32  5110.0 1695.47
  5160.0 1700.04  5200.0 1707.25  5220.0 1712.37  5250.0 1717.54  5290.0 1725.69
  5340.0 1732.52  5370.0 1737.23  5380.0 1738.26  5397.5 1741.13  5400.0 1741.13
#Mann=3,-1,0
  4745.0    0.05       0  5010.6    0.03       0  5029.3    0.05       0
Bank Sta=5010.6,5029.3
Exp/Cntr=0.3,0.1

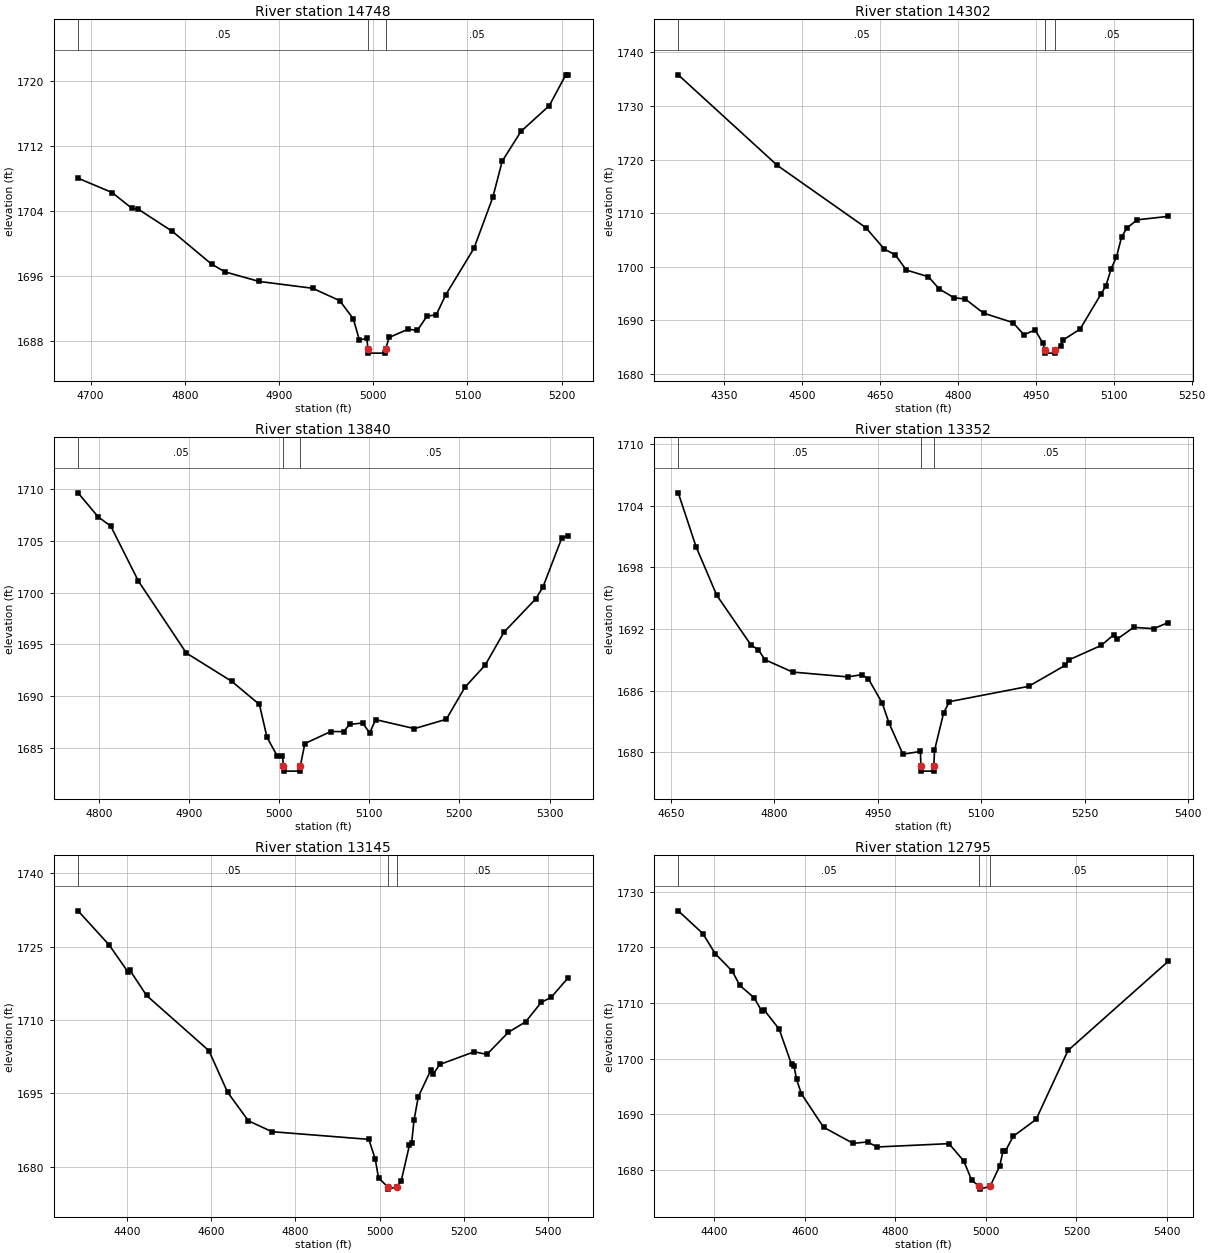
Type RM Length L Ch R = 1,14748,446,446,446
BEGIN DESCRIPTION:
South Prong Long Creek 26.0
END DESCRIPTION:
XS GIS Cut Line= 3
      1642804.97      6915937.97      1643005.00      6916188.00
      1643205.00      6916188.00
#Sta/Elev= 30
  4686.7 1708.08  4722.8 1706.32  4743.6 1704.40  4750.8 1704.25  4786.8 1701.54
  4828.4 1697.51  4842.8 1696.55  4878.8 1695.38  4935.7 1694.54  4964.5 1693.01
  4978.9 1690.77  4985.3 1688.17  4993.3 1688.39  4994.3 1687.06  4994.8 1686.56
  5012.6 1686.56  5013.1 1687.06  5016.9 1688.49  5036.9 1689.50  5046.9 1689.36
  5056.9 1691.09  5066.9 1691.28  5076.9 1693.72  5106.9 1699.45  5126.9 1705.72
  5136.9 1710.18  5156.9 1713.85  5186.9 1717.01  5204.4 1720.80  5206.9 1720.80
#Mann=3,-1,0
  4686.7    0.05       0  4994.3    0.05       0  5013.1    0.05       0
Bank Sta=4994.3,5013.1
Exp/Cntr=0.3,0.1

Type RM Length L Ch R = 1,14302,462,462,462
BEGIN DESCRIPTION:
South Prong Long Creek 25.0
END DESCRIPTION:
XS GIS Cut Line= 3
      1642104.97      6915937.97      1642655.00      6916438.00
      1642655.00      6916637.96
#Sta/Elev= 30
  4261.7 1735.83  4452.6 1718.90  4622.9 1707.28  4658.1 1703.31  4679.7 1702.19
  4700.6 1699.38  4743.2 1698.12  4764.1 1695.84  4792.5 1694.20  4814.1 1693.96
  4849.3 1691.33  4906.0 1689.56  4927.0 1687.29  4948.6 1688.19  4962.8 1685.83
  4967.6 1684.36  4968.1 1683.86  4985.9 1683.86  4986.4 1684.36  4997.9 1685.27
  5001.7 1686.27  5035.0 1688.33  5075.0 1694.82  5085.0 1696.48  5095.0 1699.63
  5105.0 1701.78  5115.0 1705.53  5125.0 1707.21  5145.0 1708.75  5205.0 1709.40
#Mann=3,-1,0
  4261.7    0.05       0  4967.6    0.03       0  4986.4    0.05       0
Bank Sta=4967.6,4986.4
Exp/Cntr=0.3,0.1

Type RM Length L Ch R = 1,13840,488,488,488
BEGIN DESCRIPTION:
South Prong Long Creek 24.0
END DESCRIPTION:
XS GIS Cut Line= 3
      1642105.02      6916288.04      1642205.00      6916488.00
      1642454.98      6916687.99
#Sta/Elev= 30
  4777.0 1709.62  4799.3 1707.30  4813.3 1706.41  4844.0 1701.10  4897.1 1694.17
  4947.5 1691.44  4978.2 1689.21  4986.6 1686.04  4997.8 1684.27  5003.8 1684.27
  5004.8 1683.28  5005.3 1682.78  5023.1 1682.78  5023.6 1683.28  5028.6 1685.44
  5057.4 1686.60  5071.8 1686.59  5078.2 1687.29  5092.6 1687.42  5100.6 1686.46
  5107.0 1687.75  5150.2 1686.88  5185.5 1687.78  5206.3 1690.88  5228.7 1693.01
  5249.5 1696.18  5284.7 1699.39  5292.7 1700.53  5313.5 1705.23  5320.7 1705.48
#Mann=3,-1,0
  4777.0    0.05       0  5004.8    0.05       0  5023.6    0.05       0
Bank Sta=5004.8,5023.6
Exp/Cntr=0.3,0.1

Type RM Length L Ch R = 1,13352,207,207,207
BEGIN DESCRIPTION:
Mapping XS 85d9ad11
END DESCRIPTION:
XS GIS Cut Line= 3
      1641832.57      6916422.06      1641832.57      6916769.32
      1642166.81      6916912.57
#Sta/Elev= 30
  4660.4 1705.24  4686.3 1699.99  4716.3 1695.27  4766.3 1690.40  4776.3 1689.99
  4786.3 1689.00  4826.3 1687.80  4906.3 1687.33  4926.3 1687.54  4936.3 1687.13
  4956.3 1684.78  4966.3 1682.81  4986.3 1679.81  5011.7 1680.07  5012.4 1678.66
  5012.9 1678.16  5030.7 1678.16  5031.2 1678.66  5032.1 1680.17  5045.4 1683.84
  5053.8 1684.92  5168.7 1686.41  5221.3 1688.44  5227.9 1689.01  5273.9 1690.39
  5292.0 1691.42  5297.4 1691.02  5321.0 1692.15  5350.0 1692.02  5371.3 1692.62
#Mann=3,-1,0
  4660.4    0.05       0  5012.4    0.03       0  5031.2    0.05       0
Bank Sta=5012.4,5031.2
Exp/Cntr=0.3,0.1

Type RM Length L Ch R = 1,13145,350,350,350
BEGIN DESCRIPTION:
South Prong Long Creek 23.0
END DESCRIPTION:
XS GIS Cut Line= 3
      1641805.01      6916137.96      1641654.62      6916837.99
      1641567.82      6917277.10
#Sta/Elev= 30
  4284.0 1732.34  4358.1 1725.33  4402.4 1719.86  4407.5 1720.14  4446.6 1715.03
  4594.7 1703.73  4639.0 1695.23  4688.4 1689.39  4744.3 1687.16  4974.4 1685.59
  4989.8 1681.48  4997.4 1677.69  5018.8 1675.91  5019.3 1675.41  5042.3 1675.91
  5051.0 1677.00  5070.8 1684.40  5075.9 1684.79  5081.6 1689.47  5091.7 1694.28
  5122.1 1699.86  5127.2 1698.94  5142.7 1700.91  5224.3 1703.50  5254.8 1702.98
  5305.8 1707.51  5346.6 1709.63  5383.5 1713.60  5407.7 1714.68  5447.6 1718.66
#Mann=3,-1,0
  4284.0    0.05       0  5018.8    0.03       0  5042.3    0.05       0
Bank Sta=5018.8,5042.3
Exp/Cntr=0.3,0.1

Type RM Length L Ch R = 1,12795,566,566,566
BEGIN DESCRIPTION:
South Prong Long Creek 22.0
END DESCRIPTION:
XS GIS Cut Line= 3
      1641505.00      6916188.00      1641305.00      6916838.00
      1641355.00      6917238.02
#Sta/Elev= 30
  4320.0 1726.54  4374.3 1722.46  4401.7 1718.84  4439.7 1715.68  4456.0 1713.14
  4487.4 1710.96  4505.1 1708.47  4510.3 1708.69  4543.0 1705.30  4570.4 1698.97
  4575.7 1698.73  4581.6 1696.26  4592.0 1693.70  4641.1 1687.67  4706.5 1684.77
  4738.5 1685.03  4759.4 1684.12  4918.3 1684.72  4951.0 1681.62  4968.7 1678.11
  4985.7 1677.05  4986.2 1676.55  5009.3 1677.05  5030.3 1680.66  5037.9 1683.39
  5042.9 1683.37  5060.5 1686.05  5110.9 1689.07  5181.5 1701.46  5403.2 1717.49
#Mann=3,-1,0
  4320.0    0.05       0  4985.7    0.05       0  5009.3    0.05       0
Bank Sta=4985.7,5009.3
Exp/Cntr=0.3,0.1