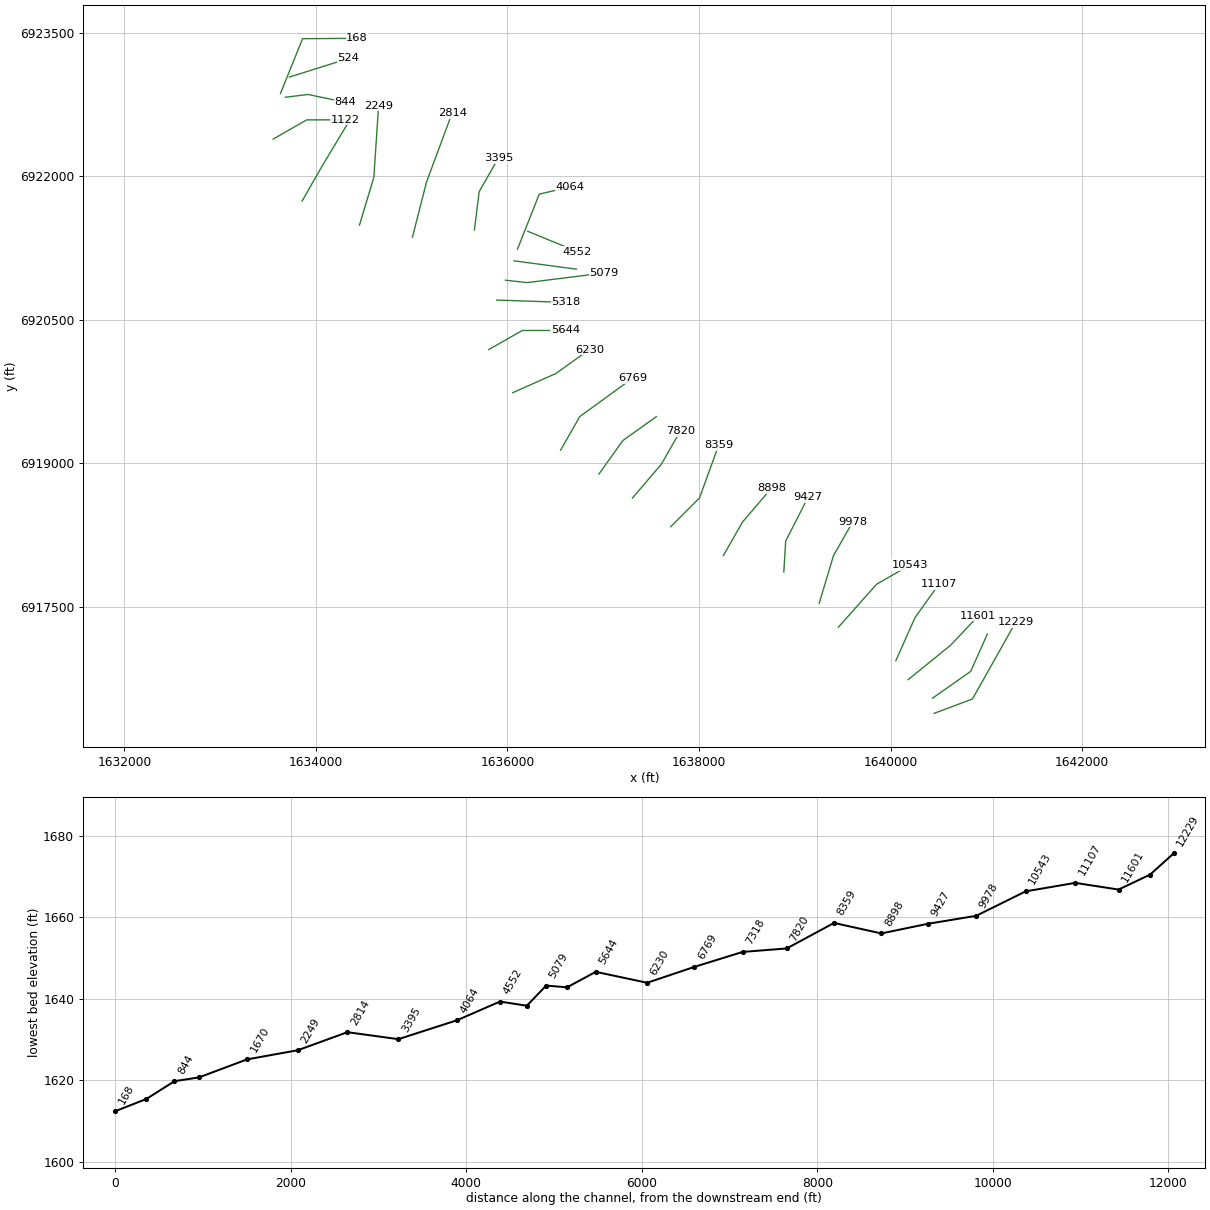
HEC-RAS study South Prong Long Creek.prj: South Prong Long Creek Base Level Engineering

--- South Prong Long Creek.g01 (geometry) --- (continued)

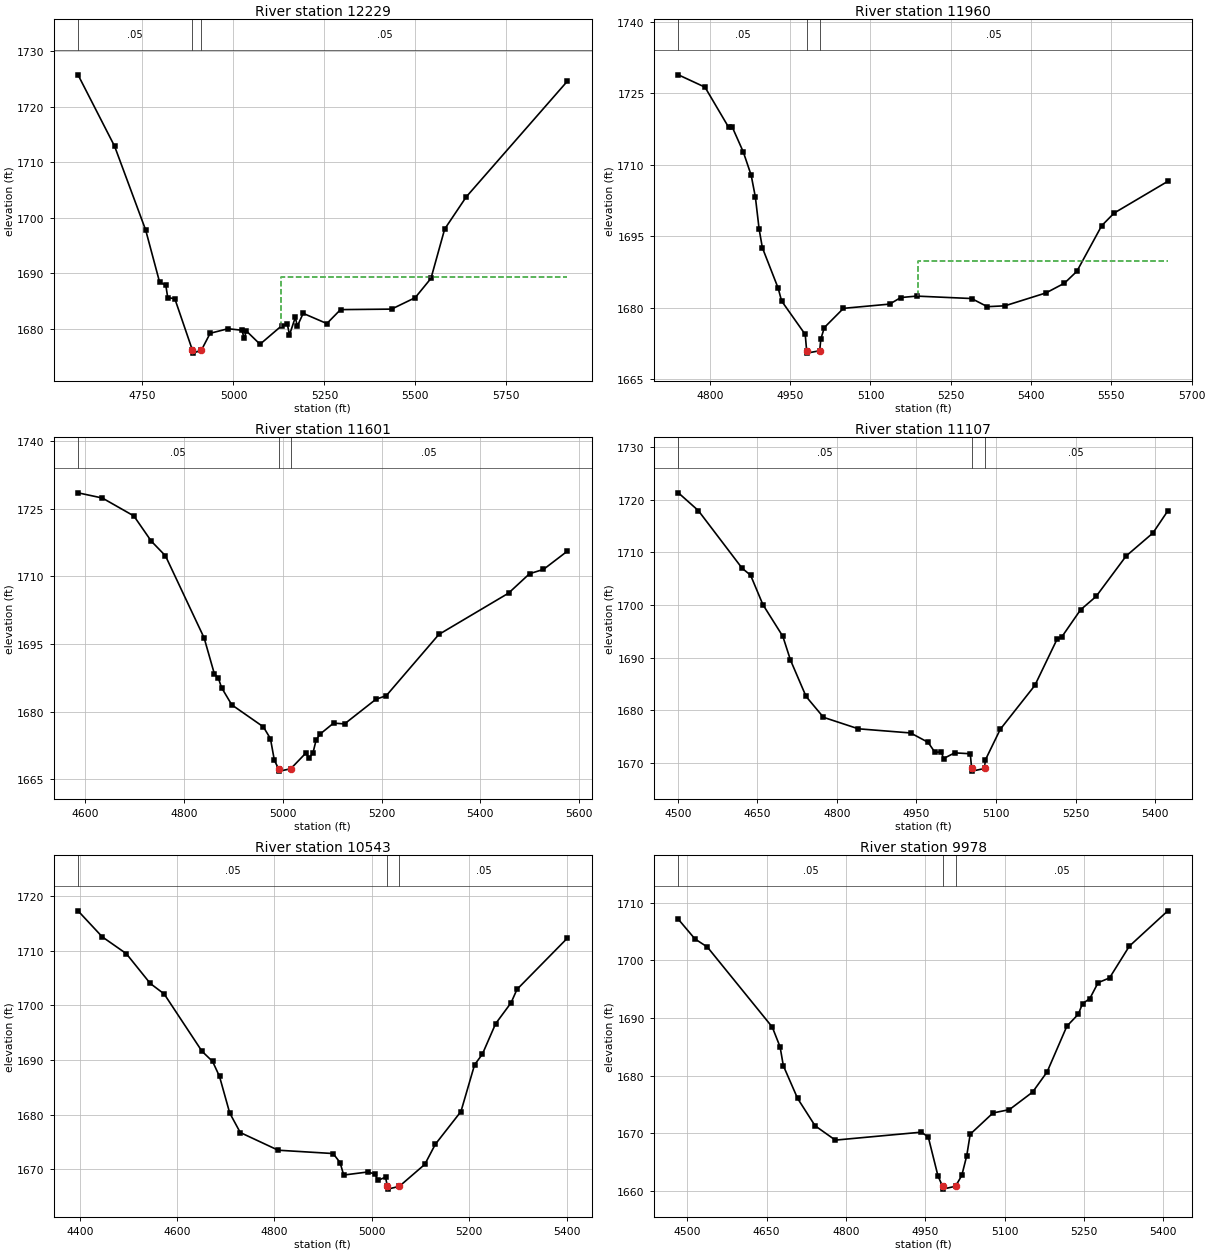
Type RM Length L Ch R = 1,12229,269,269,269
BEGIN DESCRIPTION:
South Prong Long Creek 21.0
END DESCRIPTION:
XS GIS Cut Line= 3
      1640455.00      6916388.00      1640855.00      6916538.00
      1641305.01      6917338.02
#Sta/Elev= 30
  4572.8 1725.72  4673.4 1712.86  4758.8 1697.77  4797.1 1688.39  4814.0 1687.88
  4819.3 1685.65  4838.9 1685.42  4887.3 1676.14  4887.8 1675.64  4911.6 1676.14
  4935.9 1679.21  4984.9 1680.03  5022.9 1679.76  5029.6 1678.31  5035.4 1679.63
  5073.0 1677.24  5132.3 1680.56  5148.2 1680.80  5153.9 1678.92  5169.9 1682.07
  5175.6 1680.50  5191.5 1682.80  5256.6 1680.96  5294.2 1683.47  5434.4 1683.56
  5499.4 1685.62  5542.8 1689.10  5580.4 1697.97  5639.6 1703.75  5917.9 1724.60
#Mann=3,-1,0
  4572.8    0.05       0  4887.3    0.03       0  4911.6    0.05       0
#XS Ineff=2,0
       0                 5129.40    0.00 1689.25
Permanent Ineff=
       F       F
Bank Sta=4887.3,4911.6
Exp/Cntr=0.3,0.1

Type RM Length L Ch R = 1,11960,359,359,359
BEGIN DESCRIPTION:
Mapping XS 2e5d9229
END DESCRIPTION:
XS GIS Cut Line= 3
      1640437.38      6916545.74      1640836.73      6916827.02
      1641010.32      6917215.87
#Sta/Elev= 30
  4741.2 1728.91  4790.9 1726.32  4835.3 1717.85  4841.4 1718.05  4862.4 1712.73
  4877.2 1707.82  4885.1 1703.19  4892.0 1696.54  4898.1 1692.59  4927.7 1684.06
  4934.0 1681.40  4978.2 1674.36  4980.8 1670.94  4981.3 1670.44  5005.1 1670.94
  5007.4 1673.43  5013.9 1675.82  5049.6 1679.85  5135.8 1680.74  5156.8 1682.12
  5186.3 1682.42  5288.9 1681.91  5318.3 1680.20  5351.2 1680.38  5427.9 1683.09
  5462.3 1685.13  5485.5 1687.62  5532.0 1697.22  5555.2 1699.87  5655.5 1706.54
#Mann=3,-1,0
  4741.2    0.05       0  4980.8    0.03       0  5005.1    0.05       0
#XS Ineff=2,0
       0                 5189.50    0.00 1689.83
Permanent Ineff=
       F       F
Bank Sta=4980.8,5005.1
Exp/Cntr=0.3,0.1

Type RM Length L Ch R = 1,11601,494,494,494
BEGIN DESCRIPTION:
South Prong Long Creek 20.0
END DESCRIPTION:
XS GIS Cut Line= 3
      1640183.95      6916740.21      1640628.39      6917101.32
      1640915.44      6917406.08
#Sta/Elev= 30
  4585.3 1728.53  4634.5 1727.38  4698.4 1723.40  4733.6 1717.82  4762.4 1714.55
  4840.7 1696.34  4861.5 1688.34  4869.4 1687.46  4875.9 1685.33  4896.7 1681.49
  4960.6 1676.61  4975.0 1673.99  4982.9 1669.21  4991.5 1667.28  4992.0 1666.78
  5015.9 1667.28  5046.8 1670.80  5053.3 1669.70  5061.2 1670.85  5067.6 1673.73
  5075.6 1675.00  5102.8 1677.43  5125.1 1677.26  5188.6 1682.72  5209.6 1683.52
  5316.0 1697.10  5457.2 1706.27  5499.7 1710.58  5528.0 1711.54  5576.6 1715.61
#Mann=3,-1,0
  4585.3    0.05       0  4991.5    0.05       0  5015.9    0.05       0
Bank Sta=4991.5,5015.9
Exp/Cntr=0.3,0.1

Type RM Length L Ch R = 1,11107,564,564,564
BEGIN DESCRIPTION:
South Prong Long Creek 19.0
END DESCRIPTION:
XS GIS Cut Line= 3
      1640055.01      6916938.03      1640255.00      6917388.00
      1640504.99      6917737.98
#Sta/Elev= 30
  4501.2 1721.28  4538.8 1717.91  4621.5 1706.94  4637.3 1705.64  4660.5 1700.05
  4698.1 1694.02  4712.5 1689.51  4741.9 1682.60  4774.7 1678.64  4840.4 1676.46
  4938.9 1675.67  4971.7 1673.90  4984.7 1672.01  4996.7 1672.05  5001.0 1670.81
  5021.9 1671.89  5051.4 1671.72  5053.9 1668.92  5054.4 1668.42  5078.3 1668.92
  5079.6 1670.50  5107.9 1676.37  5173.0 1684.69  5214.8 1693.45  5223.4 1693.85
  5259.1 1699.05  5288.5 1701.60  5345.1 1709.28  5395.5 1713.64  5423.7 1717.86
#Mann=3,-1,0
  4501.2    0.05       0  5053.9    0.05       0  5078.3    0.05       0
Bank Sta=5053.9,5078.3
Exp/Cntr=0.3,0.1

Type RM Length L Ch R = 1,10543,565,565,565
BEGIN DESCRIPTION:
South Prong Long Creek 18.0
END DESCRIPTION:
XS GIS Cut Line= 3
      1639454.99      6917287.99      1639855.00      6917738.00
      1640205.00      6917938.00
#Sta/Elev= 30
  4396.5 1717.33  4446.3 1712.56  4495.6 1709.49  4544.9 1704.02  4573.4 1702.10
  4651.1 1691.60  4672.9 1689.73  4687.1 1686.98  4708.0 1680.29  4729.7 1676.71
  4807.5 1673.47  4920.4 1672.86  4934.6 1671.21  4942.1 1668.92  4991.5 1669.48
  5006.5 1669.10  5012.3 1667.93  5028.1 1668.54  5031.7 1666.84  5032.2 1666.34
  5056.2 1666.84  5108.7 1670.88  5130.3 1674.56  5182.9 1680.56  5210.9 1689.13
  5226.8 1691.05  5254.1 1696.65  5285.8 1700.48  5298.0 1702.94  5401.7 1712.35
#Mann=3,-1,0
  4396.5    0.05       0  5031.7    0.05       0  5056.2    0.05       0
Bank Sta=5031.7,5056.2
Exp/Cntr=0.3,0.1

Type RM Length L Ch R = 1,9978,551,551,551
BEGIN DESCRIPTION:
South Prong Long Creek 17.0
END DESCRIPTION:
XS GIS Cut Line= 3
      1639254.99      6917537.98      1639405.00      6918038.00
      1639605.02      6918388.04
#Sta/Elev= 30
  4483.4 1707.14  4514.7 1703.74  4538.2 1702.33  4660.9 1688.45  4675.7 1685.00
  4681.8 1681.75  4708.8 1676.07  4741.8 1671.33  4780.1 1668.84  4942.8 1670.22
  4955.8 1669.37  4974.1 1662.63  4982.7 1660.84  4983.2 1660.34  5007.3 1660.84
  5019.1 1662.71  5028.5 1666.14  5035.0 1669.86  5078.1 1673.55  5109.1 1674.13
  5153.0 1677.17  5180.4 1680.67  5217.8 1688.61  5239.4 1690.68  5247.3 1692.52
  5261.0 1693.37  5276.8 1696.15  5298.4 1696.97  5335.8 1702.48  5408.6 1708.61
#Mann=3,-1,0
  4483.4    0.05       0  4982.7    0.05       0  5007.3    0.05       0
Bank Sta=4982.7,5007.3
Exp/Cntr=0.3,0.1

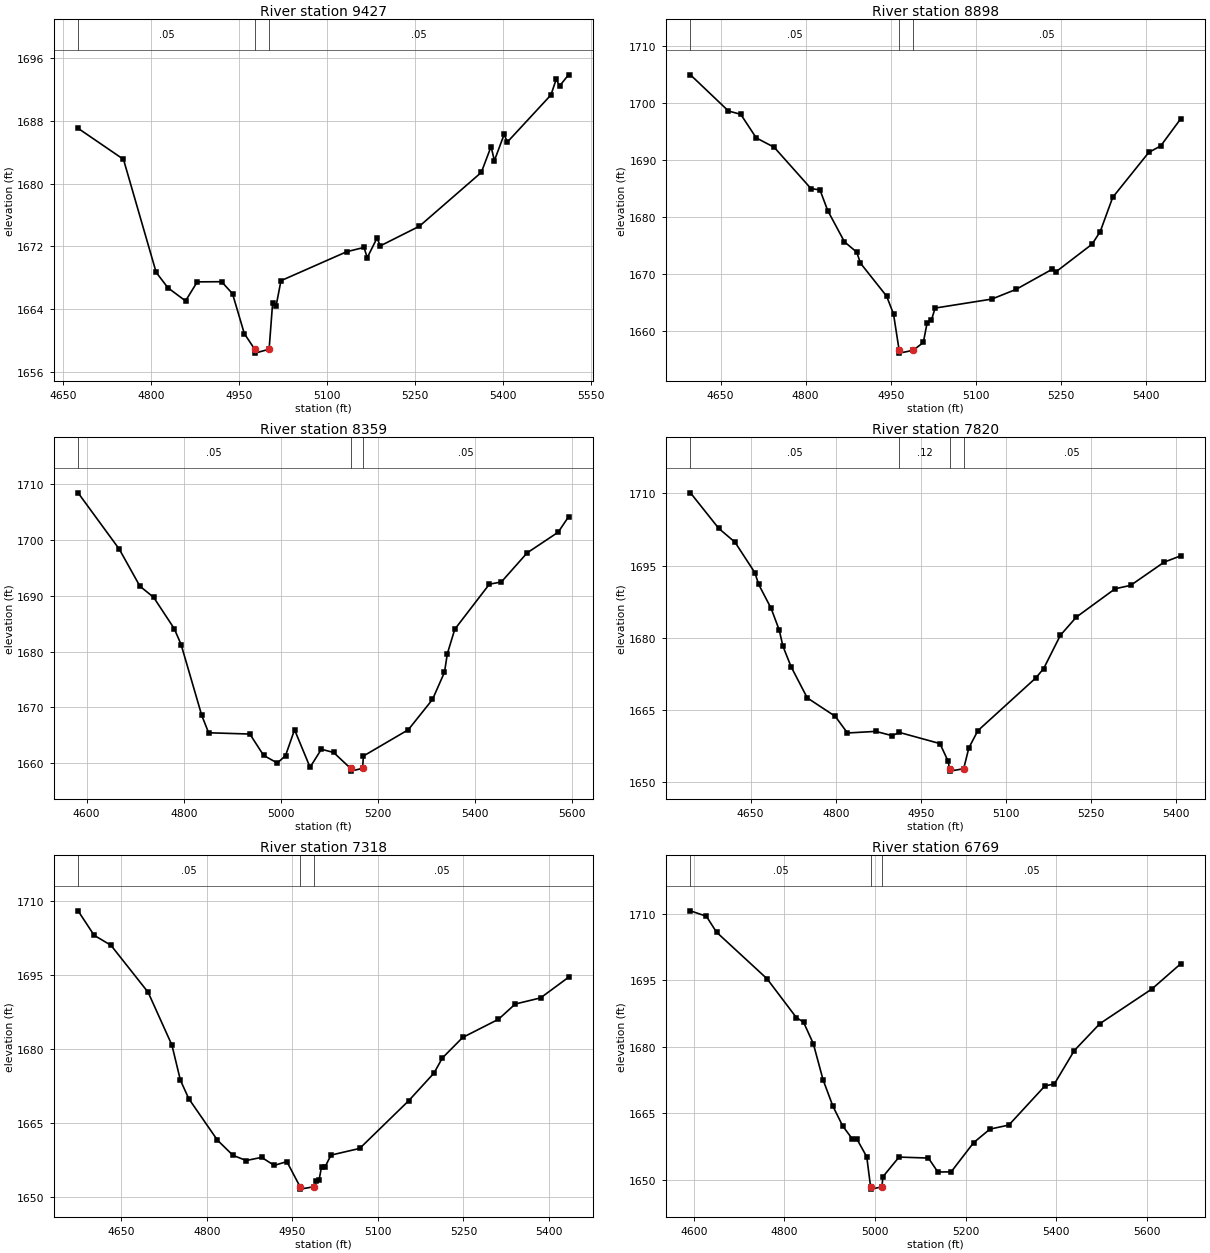
Type RM Length L Ch R = 1,9427,529,529,529
BEGIN DESCRIPTION:
South Prong Long Creek 16.0
END DESCRIPTION:
XS GIS Cut Line= 3
      1638885.33      6917865.17      1638905.00      6918188.00
      1639137.91      6918644.70
#Sta/Elev= 30
  4675.4 1687.07  4752.8 1683.11  4808.5 1668.70  4828.5 1666.73  4858.6 1665.05
  4878.6 1667.48  4920.1 1667.50  4938.7 1665.97  4958.8 1660.88  4976.5 1658.89
  4977.0 1658.39  5001.1 1658.89  5007.1 1664.80  5012.8 1664.34  5021.3 1667.63
  5133.5 1671.33  5162.8 1671.87  5168.4 1670.57  5185.0 1673.06  5190.6 1672.07
  5257.3 1674.58  5362.8 1681.44  5379.5 1684.74  5385.1 1682.94  5401.7 1686.28
  5407.3 1685.32  5481.5 1691.32  5490.6 1693.34  5496.2 1692.46  5511.5 1693.89
#Mann=3,-1,0
  4675.4    0.05       0  4976.5    0.03       0  5001.1    0.05       0
Bank Sta=4976.5,5001.1
Exp/Cntr=0.3,0.1

Type RM Length L Ch R = 1,8898,539,539,539
BEGIN DESCRIPTION:
South Prong Long Creek 15.0
END DESCRIPTION:
XS GIS Cut Line= 3
      1638254.98      6918037.96      1638455.00      6918388.00
      1638754.98      6918737.97
#Sta/Elev= 30
  4597.0 1704.95  4664.0 1698.59  4685.6 1698.01  4712.9 1693.87  4744.6 1692.21
  4809.4 1684.95  4825.2 1684.72  4838.9 1681.08  4868.4 1675.59  4890.0 1673.78
  4896.5 1671.85  4942.6 1666.05  4954.8 1662.91  4964.7 1656.53  4965.2 1656.03
  4989.5 1656.53  5007.3 1657.90  5013.9 1661.31  5021.6 1661.85  5028.1 1663.95
  5128.0 1665.53  5170.8 1667.24  5234.5 1670.78  5241.1 1670.33  5304.7 1675.19
  5319.0 1677.40  5341.0 1683.42  5404.6 1691.32  5425.5 1692.45  5461.1 1697.26
#Mann=3,-1,0
  4597.0    0.05       0  4964.7    0.03       0  4989.5    0.05       0
Bank Sta=4964.7,4989.5
Exp/Cntr=0.3,0.1

Type RM Length L Ch R = 1,8359,539,539,539
BEGIN DESCRIPTION:
South Prong Long Creek 14.0
END DESCRIPTION:
XS GIS Cut Line= 3
      1637704.98      6918337.98      1638005.00      6918638.00
      1638204.99      6919187.98
#Sta/Elev= 30
  4582.5 1708.44  4667.4 1698.34  4709.8 1691.72  4738.1 1689.72  4780.5 1684.11
  4794.7 1681.24  4837.1 1668.57  4851.2 1665.47  4936.1 1665.24  4964.4 1661.42
  4992.6 1660.05  5009.5 1661.37  5028.1 1666.01  5060.0 1659.29  5083.3 1662.52
  5108.5 1661.94  5143.3 1659.10  5143.8 1658.60  5168.2 1659.10  5169.7 1661.30
  5262.2 1666.01  5312.0 1671.43  5336.7 1676.31  5342.6 1679.63  5357.9 1684.01
  5429.1 1692.08  5453.7 1692.47  5506.9 1697.69  5570.7 1701.39  5592.0 1704.14
#Mann=3,-1,0
  4582.5    0.05       0  5143.3    0.05       0  5168.2    0.05       0
Bank Sta=5143.3,5168.2
Exp/Cntr=0.3,0.1

Type RM Length L Ch R = 1,7820,502,502,502
BEGIN DESCRIPTION:
South Prong Long Creek 13.0
END DESCRIPTION:
XS GIS Cut Line= 3
      1637304.97      6918637.97      1637605.00      6918988.00
      1637804.98      6919337.97
#Sta/Elev= 30
  4543.9 1710.13  4593.9 1702.73  4622.4 1699.88  4657.5 1693.53  4664.1 1691.12
  4686.1 1686.13  4700.3 1681.65  4706.9 1678.28  4721.2 1674.03  4749.7 1667.56
  4799.1 1663.72  4820.5 1660.27  4870.5 1660.60  4899.0 1659.72  4912.1 1660.38
  4983.5 1658.07  4997.8 1654.43  5000.4 1652.85  5000.9 1652.35  5025.3 1652.85
  5034.4 1657.17  5050.3 1660.75  5152.5 1671.71  5166.2 1673.64  5195.7 1680.56
  5223.8 1684.33  5292.1 1690.21  5319.5 1690.92  5378.5 1695.74  5408.0 1697.06
#Mann=4,-1,0
  4543.9    0.05       0  4912.1    0.12       0  5000.4    0.07       0
  5025.3    0.05       0
Bank Sta=5000.4,5025.3
Exp/Cntr=0.3,0.1

Type RM Length L Ch R = 1,7318,549,549,549
BEGIN DESCRIPTION:
South Prong Long Creek 12.0
END DESCRIPTION:
XS GIS Cut Line= 3
      1636955.01      6918888.02      1637205.00      6919238.00
      1637554.99      6919488.00
#Sta/Elev= 30
  4574.1 1708.03  4602.3 1703.06  4631.8 1701.03  4697.0 1691.48  4738.7 1680.76
  4753.5 1673.66  4768.2 1669.88  4818.6 1661.44  4845.7 1658.37  4869.0 1657.31
  4896.0 1657.95  4918.2 1656.32  4940.3 1657.09  4963.4 1652.00  4963.9 1651.50
  4988.4 1652.00  4990.7 1653.06  4996.8 1653.36  5001.1 1656.02  5007.3 1656.02
  5017.7 1658.41  5068.1 1659.77  5154.1 1669.47  5198.4 1675.08  5213.1 1678.15
  5248.7 1682.31  5311.4 1686.00  5340.9 1689.10  5385.2 1690.34  5434.3 1694.53
#Mann=3,-1,0
  4574.1    0.05       0  4963.4    0.05       0  4988.4    0.05       0
Bank Sta=4963.4,4988.4
Exp/Cntr=0.3,0.1

Type RM Length L Ch R = 1,6769,539,539,539
BEGIN DESCRIPTION:
South Prong Long Creek 11.0
END DESCRIPTION:
XS GIS Cut Line= 3
      1636555.01      6919138.02      1636755.00      6919488.00
      1637305.03      6919888.02
#Sta/Elev= 30
  4592.3 1710.72  4627.5 1709.49  4649.9 1705.90  4761.4 1695.38  4826.2 1686.61
  4842.1 1685.56  4863.7 1680.70  4885.2 1672.55  4906.8 1666.61  4928.4 1662.14
  4950.0 1659.15  4960.1 1659.12  4981.7 1655.14  4990.2 1648.34  4990.7 1647.84
  5015.2 1648.34  5017.4 1650.64  5053.0 1655.08  5117.9 1654.86  5138.7 1651.71
  5168.1 1651.74  5218.0 1658.37  5253.9 1661.40  5295.6 1662.32  5375.2 1671.16
  5396.1 1671.61  5440.1 1679.15  5496.6 1685.23  5611.7 1693.08  5675.5 1698.79
#Mann=3,-1,0
  4592.3    0.05       0  4990.2    0.03       0  5015.2    0.05       0
Bank Sta=4990.2,5015.2
Exp/Cntr=0.3,0.1

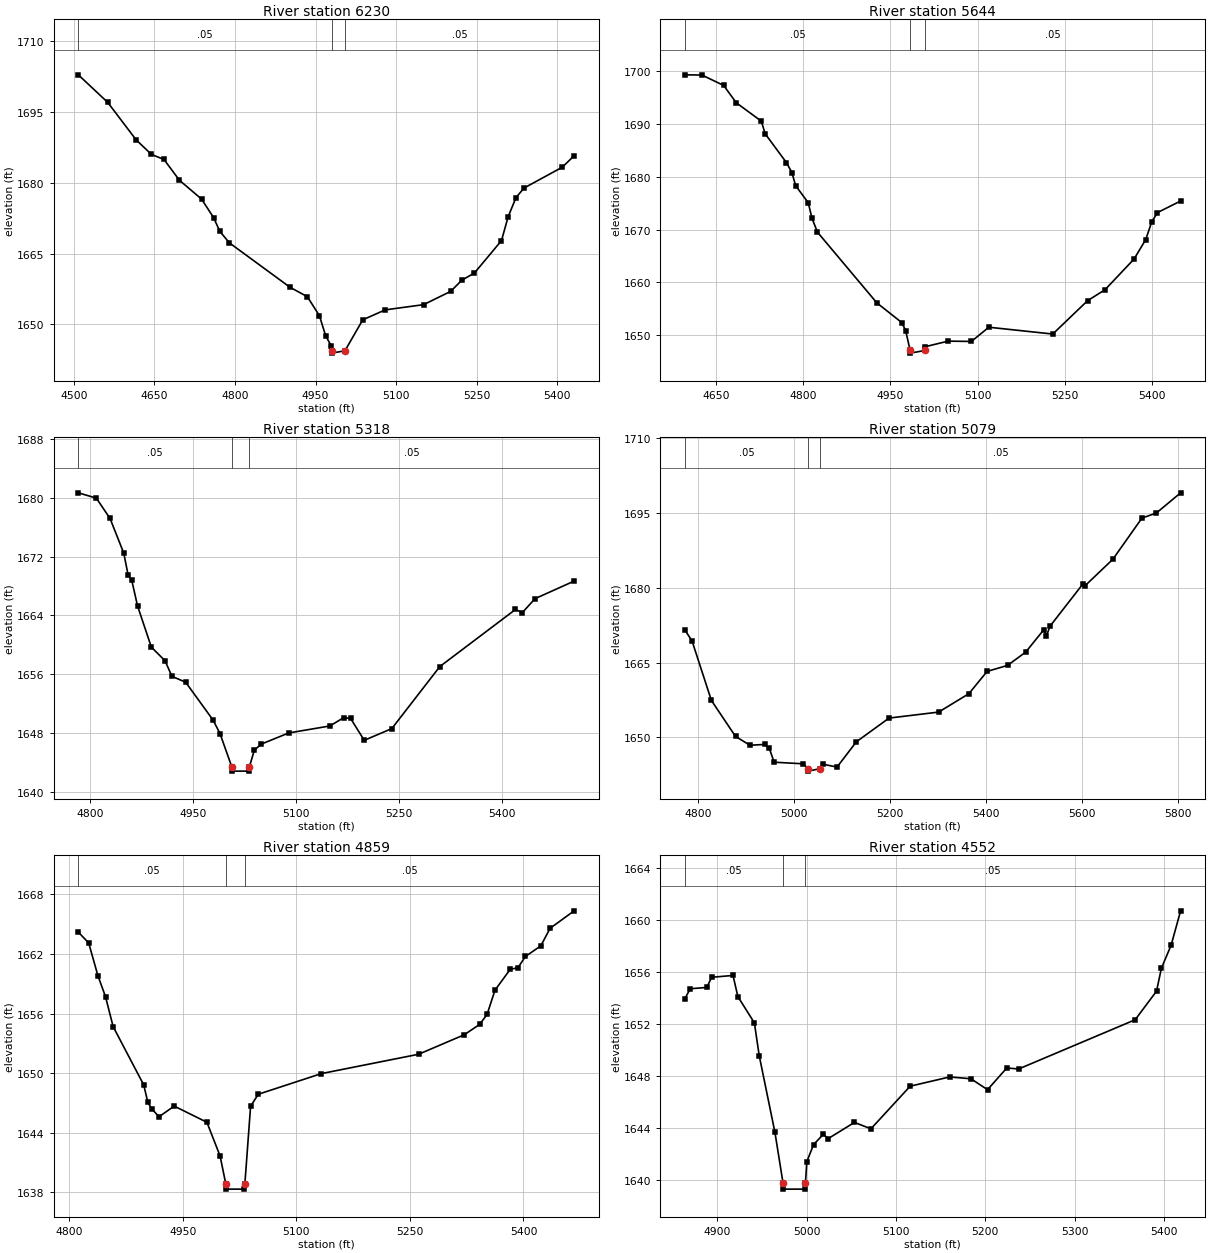
Type RM Length L Ch R = 1,6230,586,586,586
BEGIN DESCRIPTION:
South Prong Long Creek 10.0
END DESCRIPTION:
XS GIS Cut Line= 3
      1636054.97      6919737.99      1636505.00      6919938.00
      1636855.01      6920188.01
#Sta/Elev= 30
  4508.6 1702.80  4563.3 1696.97  4616.0 1689.07  4644.7 1685.96  4668.0 1684.90
  4696.7 1680.50  4737.8 1676.53  4760.3 1672.60  4772.0 1669.67  4789.7 1667.26
  4902.6 1657.86  4934.7 1655.88  4957.3 1651.83  4968.9 1647.57  4979.2 1645.48
  4979.7 1644.44  4980.2 1643.94  5004.7 1644.44  5037.9 1650.99  5079.7 1653.09
  5151.0 1654.19  5201.4 1657.00  5222.3 1659.37  5245.6 1660.88  5296.0 1667.74
  5308.3 1672.77  5323.0 1676.83  5337.8 1678.85  5409.1 1683.26  5431.2 1685.69
#Mann=3,-1,0
  4508.6    0.05       0  4979.7    0.03       0  5004.7    0.05       0
Bank Sta=4979.7,5004.7
Exp/Cntr=0.3,0.1

Type RM Length L Ch R = 1,5644,326,326,326
BEGIN DESCRIPTION:
South Prong Long Creek 9.0
END DESCRIPTION:
XS GIS Cut Line= 3
      1635805.02      6920188.01      1636155.00      6920388.00
      1636605.00      6920388.00
#Sta/Elev= 30
  4596.1 1699.27  4625.6 1699.23  4663.0 1697.26  4684.6 1693.99  4727.8 1690.50
  4734.3 1688.13  4771.0 1682.66  4780.4 1680.78  4786.8 1678.30  4808.4 1675.09
  4814.9 1672.16  4824.3 1669.51  4926.5 1656.13  4969.7 1652.38  4976.2 1650.84
  4983.8 1647.12  4984.3 1646.62  5008.9 1647.12  5009.2 1647.82  5049.2 1648.89
  5089.2 1648.83  5119.2 1651.52  5229.2 1650.23  5289.2 1656.55  5319.2 1658.62
  5369.2 1664.44  5389.2 1668.11  5399.2 1671.37  5409.2 1673.20  5449.2 1675.40
#Mann=3,-1,0
  4596.1    0.05       0  4983.8    0.03       0  5008.9    0.05       0
Bank Sta=4983.8,5008.9
Exp/Cntr=0.3,0.1

Type RM Length L Ch R = 1,5318,239,239,239
BEGIN DESCRIPTION:
Mapping XS 8bfaa3f6
END DESCRIPTION:
XS GIS Cut Line= 2
      1635888.81      6920705.49      1636610.50      6920681.20
#Sta/Elev= 30
  4782.9 1680.67  4809.1 1679.95  4829.1 1677.18  4849.1 1672.46  4855.5 1669.44
  4860.5 1668.86  4869.1 1665.30  4889.2 1659.70  4909.2 1657.83  4919.2 1655.72
  4939.2 1654.92  4979.2 1649.76  4989.2 1647.94  5006.7 1643.33  5007.2 1642.83
  5031.3 1642.83  5031.8 1643.33  5039.2 1645.68  5049.2 1646.50  5089.3 1648.02
  5149.2 1648.97  5169.3 1650.10  5179.3 1650.01  5199.3 1647.02  5239.4 1648.61
  5309.4 1657.05  5419.5 1664.81  5429.5 1664.38  5448.0 1666.28  5505.0 1668.67
#Mann=3,-1,0
  4782.9    0.05       0  5006.7    0.05       0  5031.8    0.05       0
Bank Sta=5006.7,5031.8
Exp/Cntr=0.3,0.1

Type RM Length L Ch R = 1,5079,220,220,220
BEGIN DESCRIPTION:
South Prong Long Creek 8.0
END DESCRIPTION:
XS GIS Cut Line= 3
      1635980.00      6920913.00      1636205.00      6920888.00
      1637004.99      6920988.00
#Sta/Elev= 30
  4772.2 1671.58  4787.3 1669.35  4827.5 1657.44  4877.8 1650.21  4908.0 1648.44
  4938.2 1648.60  4948.3 1647.79  4958.3 1645.04  5018.7 1644.72  5028.9 1643.75
  5029.4 1643.25  5054.0 1643.75  5059.1 1644.64  5089.3 1644.07  5129.6 1649.14
  5197.6 1653.89  5300.9 1655.09  5363.9 1658.79  5401.7 1663.24  5444.5 1664.46
  5482.3 1667.13  5520.1 1671.64  5525.2 1670.33  5532.7 1672.30  5600.7 1680.72
  5605.8 1680.43  5663.7 1685.74  5724.2 1693.99  5754.4 1695.02  5804.8 1699.06
#Mann=3,-1,0
  4772.2    0.05       0  5028.9    0.03       0  5054.0    0.05       0
Bank Sta=5028.9,5054
Exp/Cntr=0.3,0.1

Type RM Length L Ch R = 1,4859,307,307,307
BEGIN DESCRIPTION:
Mapping XS bb865d39
END DESCRIPTION:
XS GIS Cut Line= 2
      1636069.38      6921115.21      1636718.70      6921028.40
#Sta/Elev= 30
  4811.9 1664.20  4825.6 1663.10  4837.8 1659.80  4847.8 1657.70  4857.9 1654.68
  4898.3 1648.81  4903.7 1647.08  4908.7 1646.42  4918.5 1645.61  4938.6 1646.68
  4981.8 1645.05  4999.2 1641.65  5006.8 1638.82  5007.3 1638.32  5031.4 1638.32
  5031.9 1638.82  5039.5 1646.66  5049.6 1647.87  5132.9 1649.95  5261.5 1651.90
  5322.0 1653.87  5342.2 1654.91  5352.0 1655.92  5362.4 1658.35  5382.6 1660.46
  5392.6 1660.60  5402.7 1661.75  5422.9 1662.81  5435.2 1664.58  5467.0 1666.34
#Mann=3,-1,0
  4811.9    0.05       0  5006.8    0.03       0  5031.9    0.05       0
Bank Sta=5006.8,5031.9
Exp/Cntr=0.3,0.1

Type RM Length L Ch R = 1,4552,488,488,488
BEGIN DESCRIPTION:
Mapping XS 56873142
END DESCRIPTION:
XS GIS Cut Line= 2
      1636211.71      6921424.25      1636724.92      6921212.72
#Sta/Elev= 30
  4863.7 1653.94  4869.8 1654.71  4888.3 1654.81  4893.8 1655.59  4917.7 1655.73
  4923.1 1654.11  4941.6 1652.09  4947.0 1649.58  4964.6 1643.69  4973.6 1639.83
  4974.1 1639.33  4998.3 1639.33  4998.8 1639.83  5000.3 1641.44  5007.9 1642.75
  5018.7 1643.53  5024.3 1643.21  5053.6 1644.45  5072.1 1643.96  5116.0 1647.23
  5160.2 1647.94  5184.1 1647.80  5202.6 1646.96  5224.2 1648.63  5237.4 1648.55
  5367.9 1652.33  5391.8 1654.52  5397.3 1656.29  5408.1 1658.04  5418.8 1660.69
#Mann=3,-1,0
  4863.7    0.05       0  4973.6    0.05       0  4998.8    0.05       0
Bank Sta=4973.6,4998.8
Exp/Cntr=0.3,0.1

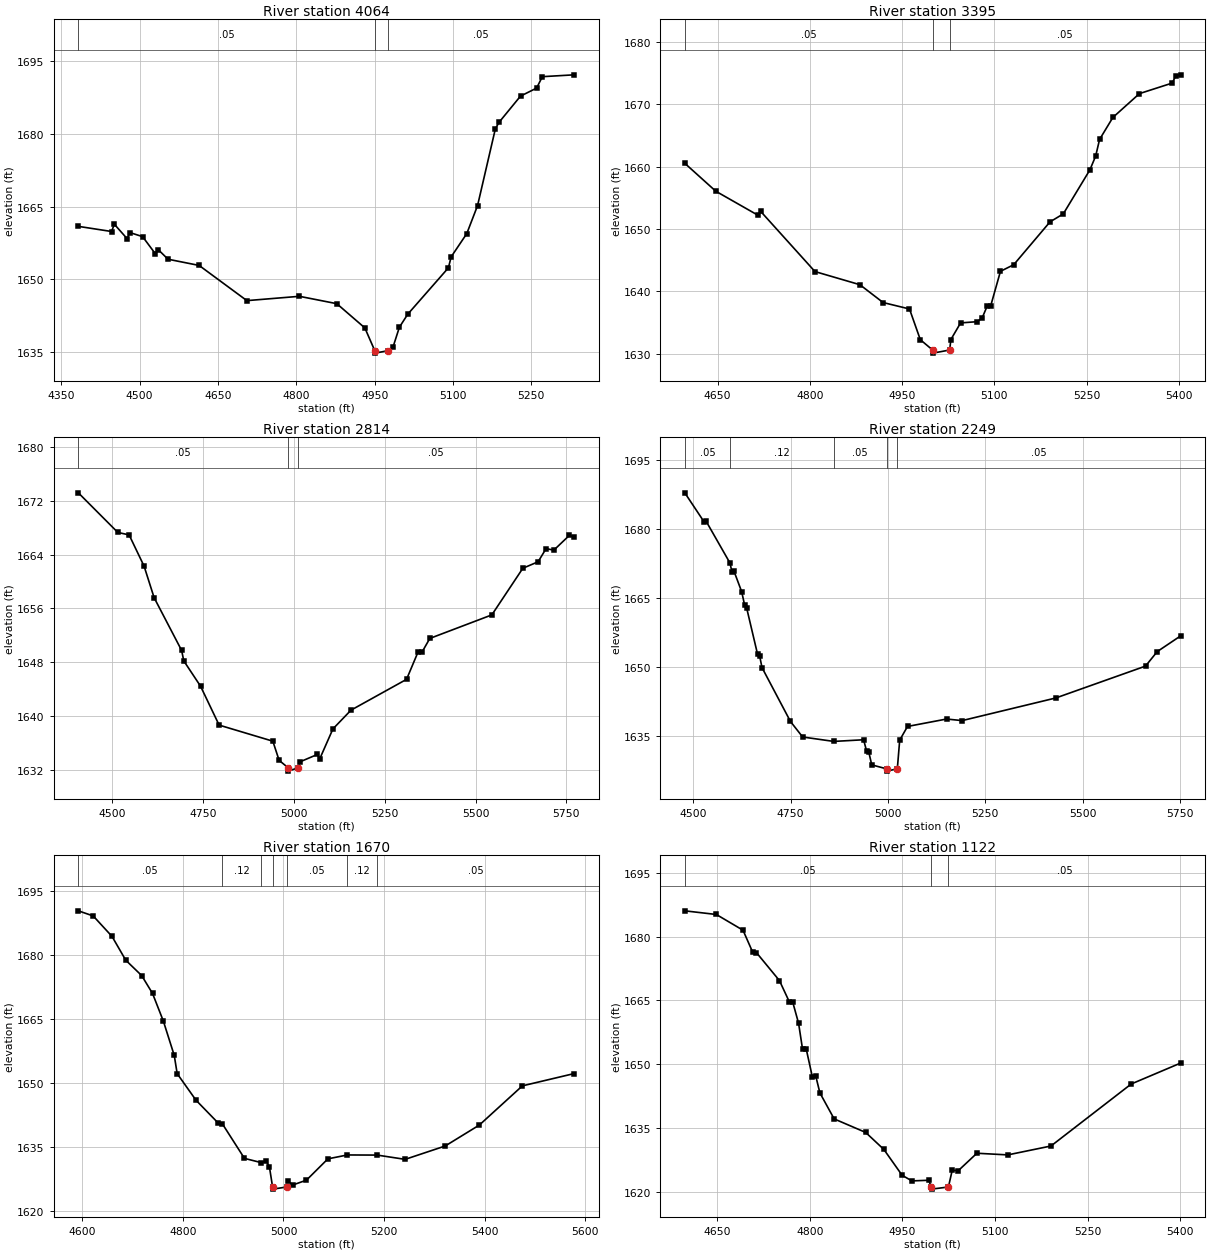
Type RM Length L Ch R = 1,4064,669,669,669
BEGIN DESCRIPTION:
South Prong Long Creek 7.0
END DESCRIPTION:
XS GIS Cut Line= 3
      1636105.00      6921238.00      1636331.94      6921811.86
      1636654.99      6921888.00
#Sta/Elev= 30
  4382.9 1660.91  4446.5 1659.85  4451.8 1661.35  4476.2 1658.38  4481.6 1659.63
  4505.9 1658.79  4530.3 1655.26  4535.6 1656.13  4554.6 1654.13  4614.1 1652.85
  4705.5 1645.59  4806.0 1646.48  4877.6 1644.96  4931.3 1639.96  4950.3 1635.26
  4950.8 1634.76  4975.5 1635.26  4985.1 1635.97  4997.4 1640.11  5013.4 1642.79
  5091.3 1652.37  5096.4 1654.61  5126.4 1659.42  5147.0 1665.19  5181.1 1681.04
  5188.1 1682.37  5229.2 1687.78  5260.0 1689.43  5271.0 1691.79  5331.9 1692.17
#Mann=3,-1,0
  4382.9    0.05       0  4950.3    0.05       0  4975.5    0.05       0
Bank Sta=4950.3,4975.5
Exp/Cntr=0.3,0.1

Type RM Length L Ch R = 1,3395,581,581,581
BEGIN DESCRIPTION:
South Prong Long Creek 6.0
END DESCRIPTION:
XS GIS Cut Line= 3
      1635654.99      6921437.96      1635705.00      6921838.00
      1635905.02      6922188.03
#Sta/Elev= 30
  4596.6 1660.52  4647.0 1656.05  4715.1 1652.23  4720.1 1652.81  4808.3 1643.18
  4881.3 1641.08  4919.1 1638.22  4962.0 1637.19  4979.6 1632.27  4999.6 1630.62
  5000.1 1630.12  5027.3 1630.62  5029.3 1632.30  5045.1 1634.96  5072.5 1635.16
  5080.4 1635.81  5088.3 1637.65  5094.1 1637.71  5109.9 1643.22  5131.5 1644.28
  5190.5 1651.14  5212.1 1652.42  5255.3 1659.46  5264.7 1661.67  5271.1 1664.34
  5292.7 1667.86  5335.9 1671.68  5389.2 1673.37  5394.9 1674.50  5402.9 1674.69
#Mann=3,-1,0
  4596.6    0.05       0  4999.6    0.05       0  5027.3    0.05       0
Bank Sta=4999.6,5027.3
Exp/Cntr=0.3,0.1

Type RM Length L Ch R = 1,2814,565,565,565
BEGIN DESCRIPTION:
South Prong Long Creek 5.0
END DESCRIPTION:
XS GIS Cut Line= 3
      1635007.94      6921362.67      1635155.00      6921938.00
      1635422.97      6922660.37
#Sta/Elev= 30
  4407.0 1673.19  4515.7 1667.30  4546.7 1666.94  4588.0 1662.28  4615.5 1657.61
  4691.2 1649.77  4697.2 1648.21  4743.2 1644.46  4794.4 1638.67  4942.2 1636.28
  4959.5 1633.43  4984.3 1632.33  4984.8 1631.83  5012.1 1632.33  5016.0 1633.19
  5064.8 1634.31  5071.4 1633.67  5107.5 1638.10  5157.2 1640.89  5310.1 1645.47
  5342.1 1649.58  5352.8 1649.53  5374.1 1651.55  5544.8 1655.05  5630.1 1661.98
  5672.0 1662.94  5694.1 1664.90  5715.4 1664.67  5757.8 1666.85  5771.3 1666.61
#Mann=3,-1,0
  4407.0    0.05       0  4984.3    0.03       0  5012.1    0.05       0
Bank Sta=4984.3,5012.1
Exp/Cntr=0.3,0.1

Type RM Length L Ch R = 1,2249,579,579,579
BEGIN DESCRIPTION:
South Prong Long Creek 4.0
END DESCRIPTION:
XS GIS Cut Line= 3
      1634455.01      6921488.04      1634605.00      6921988.00
      1634655.00      6922737.97
#Sta/Elev= 30
  4478.2 1687.83  4527.7 1681.53  4533.0 1681.66  4594.3 1672.58  4599.1 1670.72
  4604.3 1670.88  4624.3 1666.36  4632.1 1663.37  4637.4 1662.72  4665.2 1652.75
  4670.4 1652.44  4676.5 1649.89  4749.6 1638.19  4780.9 1634.82  4860.9 1633.86
  4937.5 1634.22  4945.4 1631.69  4950.6 1631.61  4958.4 1628.77  4996.3 1627.91
  4996.8 1627.41  5024.1 1627.91  5030.2 1634.14  5050.3 1637.11  5150.5 1638.72
  5190.6 1638.38  5431.1 1643.29  5661.6 1650.21  5691.7 1653.36  5751.8 1656.77
#Mann=5,-1,0
  4478.2    0.05       0  4594.3    0.12       0  4860.9    0.05       0
  4996.3    0.05       0  5024.1    0.05       0
Bank Sta=4996.3,5024.1
Exp/Cntr=0.3,0.1

Type RM Length L Ch R = 1,1670,548,548,548
BEGIN DESCRIPTION:
South Prong Long Creek 3.0
END DESCRIPTION:
XS GIS Cut Line= 3
      1633854.98      6921737.97      1634055.00      6922088.00
      1634354.98      6922587.96
#Sta/Elev= 30
  4592.0 1690.40  4621.6 1689.20  4659.0 1684.40  4686.3 1678.83  4718.0 1675.22
  4739.6 1671.03  4761.2 1664.52  4782.8 1656.49  4788.6 1652.23  4826.0 1646.01
  4869.2 1640.77  4878.1 1640.54  4922.4 1632.37  4954.9 1631.40  4965.6 1631.77
  4972.1 1630.35  4978.4 1625.66  4978.9 1625.16  5006.2 1625.66  5008.8 1627.09
  5018.5 1626.13  5045.7 1627.26  5088.4 1632.26  5127.3 1633.17  5186.4 1633.14
  5242.0 1632.14  5321.7 1635.27  5389.7 1640.19  5475.2 1649.37  5578.2 1652.25
#Mann=7,-1,0
  4592.0    0.05       0  4878.1    0.12       0  4954.9    0.05       0
  4978.4    0.03       0  5006.2    0.05       0  5127.3    0.12       0
  5186.4    0.05       0
Bank Sta=4978.4,5006.2
Exp/Cntr=0.3,0.1

Type RM Length L Ch R = 1,1122,278,278,278
BEGIN DESCRIPTION:
South Prong Long Creek 2.0
END DESCRIPTION:
XS GIS Cut Line= 3
      1633555.01      6922388.01      1633905.00      6922588.00
      1634305.00      6922588.00
#Sta/Elev= 30
  4597.4 1686.04  4648.5 1685.18  4691.7 1681.49  4707.5 1676.28  4713.3 1676.26
  4750.7 1669.67  4766.5 1664.75  4772.3 1664.58  4781.7 1659.65  4788.1 1653.59
  4793.9 1653.73  4804.0 1647.08  4809.7 1647.17  4816.2 1643.32  4839.3 1637.22
  4890.4 1634.04  4919.9 1630.04  4949.4 1623.99  4965.2 1622.67  4992.6 1622.82
  4996.5 1621.24  4997.0 1620.74  5024.4 1621.24  5030.5 1625.15  5040.5 1625.09
  5070.5 1629.16  5120.5 1628.77  5190.5 1630.86  5320.5 1645.41  5400.5 1650.32
#Mann=3,-1,0
  4597.4    0.05       0  4996.5    0.05       0  5024.4    0.05       0
Bank Sta=4996.5,5024.4
Exp/Cntr=0.3,0.1

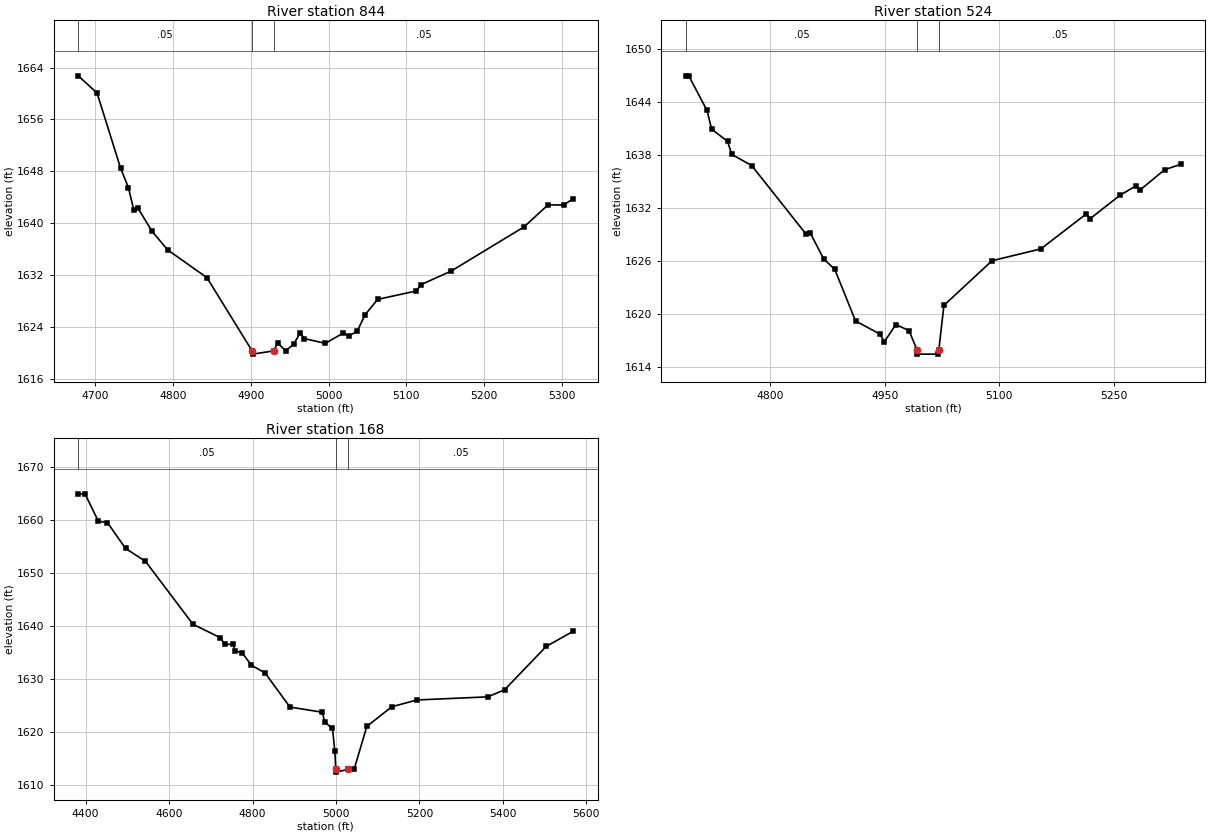
Type RM Length L Ch R = 1,844,320,320,320
BEGIN DESCRIPTION:
Mapping XS 135260b1
END DESCRIPTION:
XS GIS Cut Line= 3
      1633680.95      6922824.06      1633917.71      6922853.30
      1634306.43      6922771.46
#Sta/Elev= 30
  4678.4 1662.72  4702.6 1660.06  4732.9 1648.44  4742.9 1645.48  4749.6 1642.09
  4754.7 1642.40  4773.2 1638.76  4793.3 1635.89  4843.7 1631.62  4901.8 1620.33
  4902.3 1619.83  4929.7 1620.33  4934.6 1621.56  4944.8 1620.35  4955.1 1621.32
  4963.6 1623.13  4968.7 1622.23  4995.9 1621.49  5018.5 1623.05  5026.6 1622.67
  5036.8 1623.36  5047.0 1625.90  5063.2 1628.27  5113.0 1629.57  5118.6 1630.52
  5157.7 1632.64  5251.4 1639.45  5282.1 1642.84  5302.1 1642.80  5314.2 1643.77
#Mann=3,-1,0
  4678.4    0.05       0  4901.8    0.03       0  4929.7    0.05       0
Bank Sta=4901.8,4929.7
Exp/Cntr=0.3,0.1

Type RM Length L Ch R = 1,524,356,356,356
BEGIN DESCRIPTION:
Mapping XS 6f42221c
END DESCRIPTION:
XS GIS Cut Line= 2
      1633722.97      6923034.93      1634340.53      6923229.22
#Sta/Elev= 30
  4689.8 1646.97  4693.5 1646.97  4717.4 1643.05  4723.4 1640.93  4744.3 1639.55
  4749.8 1638.07  4775.8 1636.82  4847.0 1629.05  4852.2 1629.23  4870.1 1626.24
  4884.6 1625.06  4911.7 1619.22  4943.5 1617.75  4949.4 1616.87  4964.5 1618.81
  4981.7 1618.14  4992.1 1615.97  4992.6 1615.47  5020.2 1615.47  5020.7 1615.97
  5027.4 1620.99  5090.3 1626.04  5154.2 1627.38  5213.7 1631.34  5218.9 1630.81
  5258.0 1633.47  5278.5 1634.50  5283.7 1634.02  5316.1 1636.34  5337.2 1636.95
#Mann=3,-1,0
  4689.8    0.05       0  4992.1    0.05       0  5020.7    0.05       0
Bank Sta=4992.1,5020.7
Exp/Cntr=0.3,0.1

Type RM Length L Ch R = 1,168,0,0,0
BEGIN DESCRIPTION:
South Prong Long Creek 1.0
END DESCRIPTION:
XS GIS Cut Line= 3
      1633630.02      6922863.05      1633861.07      6923435.80
      1634429.05      6923439.60
#Sta/Elev= 30
  4382.4 1664.93  4398.5 1664.96  4430.6 1659.77  4452.4 1659.53  4495.6 1654.66
  4543.4 1652.23  4657.3 1640.35  4722.0 1637.85  4734.0 1636.56  4752.8 1636.58
  4758.2 1635.39  4775.9 1634.89  4797.5 1632.60  4829.8 1631.19  4889.7 1624.73
  4967.5 1623.76  4972.9 1621.88  4991.6 1620.71  4997.1 1616.49  4999.6 1612.96
  5000.1 1612.46  5028.3 1612.96  5043.9 1613.12  5073.9 1621.08  5133.9 1624.80
  5193.9 1626.07  5363.9 1626.66  5403.9 1627.99  5503.9 1636.18  5568.0 1639.01
#Mann=3,-1,0
  4382.4    0.05       0  4999.6    0.05       0  5028.3    0.05       0
Bank Sta=4999.6,5028.3
Exp/Cntr=0.3,0.1

Chan Stop Cuts=-1