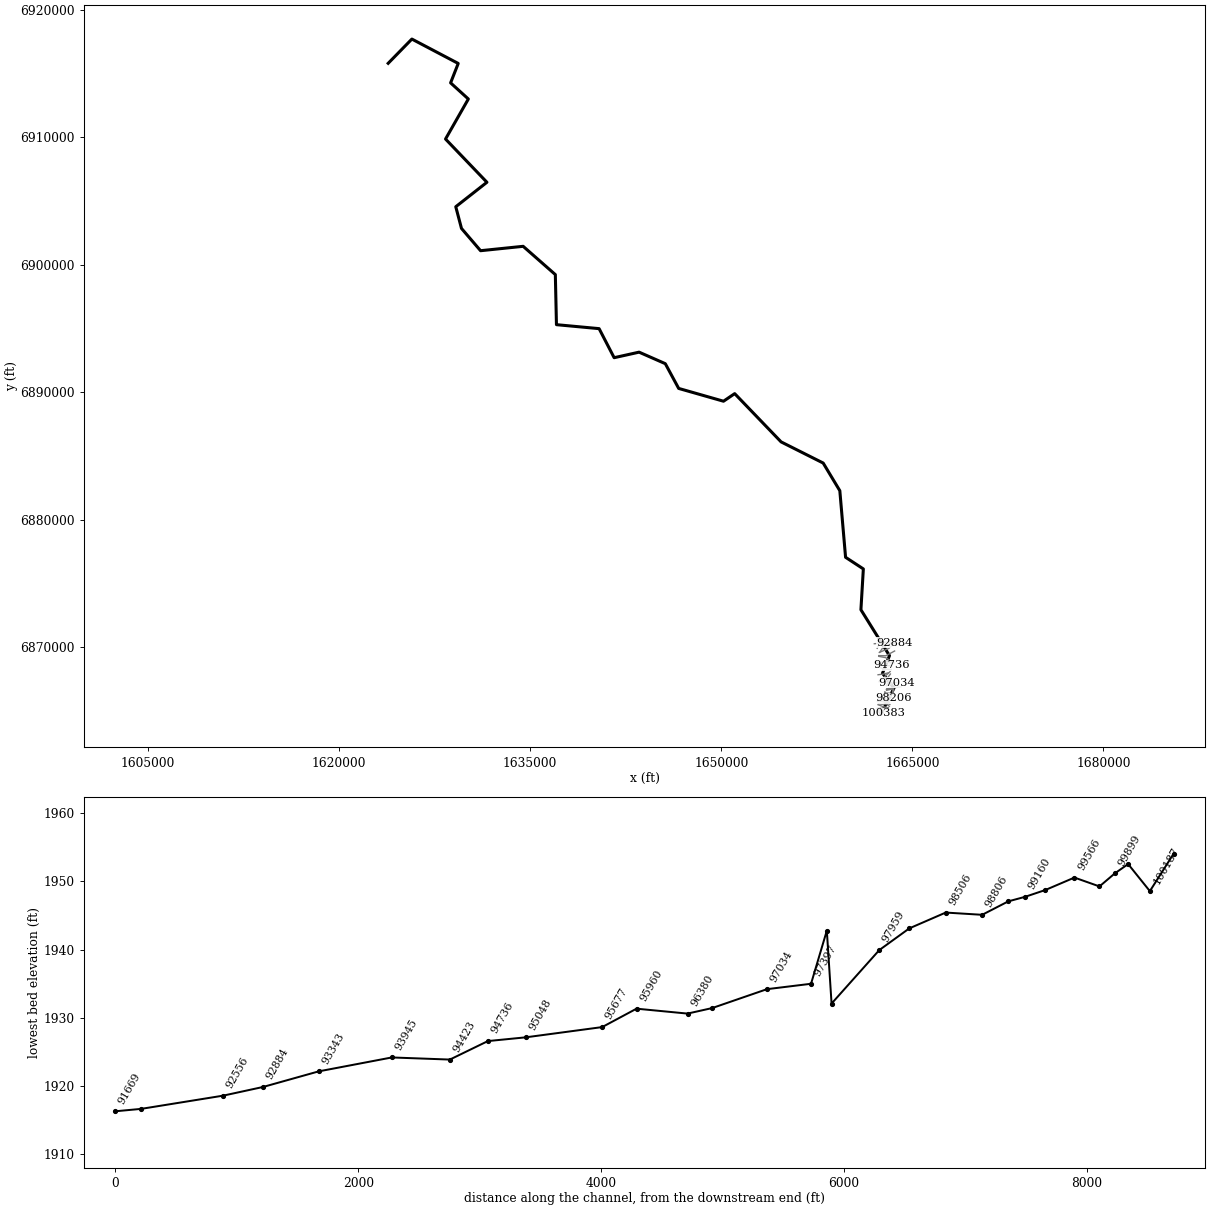
--- Spring Creek.prj (project) ---

Proj Title=Spring Creek Base Level Engineering
Current Plan=p01
Default Exp/Contr=0.3,0.1
English Units
Geom File=g01
Flow File=f01
Plan File=p01
BEGIN DESCRIPTION:
Spring Creek
END DESCRIPTION:

--- Spring Creek.p01 (plan) ---

Plan Title=Multiple Run
Short Identifier=Multiple
Geom File=g01
Flow File=f01
Subcritical Flow
K Sum by GR= 0
Std Step Tol= 0.01
Critical Tol= 0.01
Num of Std Step Trials= 20
Max Error Tol= 0.3
Flow Tol Ratio= 0.001
Split Flow NTrial= 30
Split Flow Tol= 0.02
Split Flow Ratio= 0.02
Log Output Level= 0
Friction Slope Method= 1
Unsteady Friction Slope Method= 2
Unsteady Bridges Friction Slope Method= 1
Parabolic Critical Depth
Global Vel Dist=  1 , 1 , 1
Global Log Level= 0
CheckData=True
Encroach Param= -1, 0, 0, 0
BEGIN DESCRIPTION:
Multiple Run
END DESCRIPTION:

--- Spring Creek.f01 (steady flow) ---

Flow Title=Multiple
Number of Profiles=7
Profile Names=10-year,25-year,50-year,1pct_min,100-year,1pct_plu,500-year
River Rch & RM= Spring Creek,Reach-1,100383
     247     341     418     255     509    1015     764
River Rch & RM= Spring Creek,Reach-1,100187
     250     343     420     256     510    1018     763
River Rch & RM= Spring Creek,Reach-1,97397
     462     655     816     506    1009    2014    1563
River Rch & RM= Spring Creek,Reach-1,90874
     490     695     867     538    1073    2141    1664
River Rch & RM= Spring Creek,Reach-1,89536
     576     822    1032     643    1283    2559    2009
River Rch & RM= Spring Creek,Reach-1,87573
     650     934    1175     734    1464    2922    2306
River Rch & RM= Spring Creek,Reach-1,81944
     690     993    1252     783    1562    3116    2465
River Rch & RM= Spring Creek,Reach-1,80133
     761    1098    1388     870    1736    3464    2753
River Rch & RM= Spring Creek,Reach-1,76447
    1008    1473    1878    1186    2366    4722    3811
River Rch & RM= Spring Creek,Reach-1,71559
    1061    1553    1982    1254    2502    4991    4038
River Rch & RM= Spring Creek,Reach-1,68037
    1132    1663    2127    1348    2689    5365    4357
River Rch & RM= Spring Creek,Reach-1,62501
    1147    1685    2154    1364    2722    5431    4408
River Rch & RM= Spring Creek,Reach-1,58468
    1203    1770    2264    1435    2864    5714    4645
River Rch & RM= Spring Creek,Reach-1,55990
    1260    1856    2378    1510    3012    6010    4898
River Rch & RM= Spring Creek,Reach-1,50703
    1472    2180    2803    1785    3561    7105    5825
River Rch & RM= Spring Creek,Reach-1,47877
    1603    2379    3064    1953    3897    7775    6390
River Rch & RM= Spring Creek,Reach-1,44007
    2392    3601    4683    3014    6013   11997   10043
River Rch & RM= Spring Creek,Reach-1,39491
    2359    3542    4597    2952    5891   11753    9799
River Rch & RM= Spring Creek,Reach-1,31821
    2394    3595    4669    2999    5983   11938    9958
River Rch & RM= Spring Creek,Reach-1,29613
    2391    3587    4653    2986    5958   11887    9894
River Rch & RM= Spring Creek,Reach-1,23289
    2423    3635    4715    3026    6037   12045   10026
River Rch & RM= Spring Creek,Reach-1,18395
    2431    3646    4728    3032    6050   12072   10040
River Rch & RM= Spring Creek,Reach-1,13189
    2705    4068    5285    3396    6776   13521   11283
River Rch & RM= Spring Creek,Reach-1,9891
    2722    4092    5316    3415    6814   13595   11340
River Rch & RM= Spring Creek,Reach-1,6597
    2745    4125    5359    3442    6867   13702   11425
River Rch & RM= Spring Creek,Reach-1,1430
    2744    4122    5353    3438    6860   13687   11409
Boundary for River Rch & Prof#=Spring Creek,Reach-1,1
Up Type=0
Dn Type=3
Dn Slope=0.007
Boundary for River Rch & Prof#=Spring Creek,Reach-1,2
Up Type=0
Dn Type=3
Dn Slope=0.007
Boundary for River Rch & Prof#=Spring Creek,Reach-1,3
Up Type=0
Dn Type=3
Dn Slope=0.007
Boundary for River Rch & Prof#=Spring Creek,Reach-1,4
Up Type=0
Dn Type=3
Dn Slope=0.007
Boundary for River Rch & Prof#=Spring Creek,Reach-1,5
Up Type=0
Dn Type=3
Dn Slope=0.007
Boundary for River Rch & Prof#=Spring Creek,Reach-1,6
Up Type=0
Dn Type=3
Dn Slope=0.007
Boundary for River Rch & Prof#=Spring Creek,Reach-1,7
Up Type=0
Dn Type=3
Dn Slope=0.007

--- Spring Creek.g01 (geometry) ---

Geom Title=Existing Conditions

River Reach=Spring Creek,Reach-1
Reach XY= 30
      1662555.00      6864788.00      1663555.00      6866788.00
      1662655.38      6867953.28      1663202.00      6869336.59
      1660960.52      6872935.57      1661151.45      6876136.53
      1659756.48      6877049.48      1659305.07      6882269.88
      1657999.17      6884440.30      1654695.32      6886098.76
      1651053.31      6889883.85      1650175.28      6889288.26
      1646656.55      6890291.75      1645607.44      6892232.48
      1643549.32      6893136.01      1641591.34      6892701.26
      1640411.12      6894979.92      1637063.09      6895291.35
      1636975.52      6899218.53      1634449.14      6901435.94
      1631106.55      6901091.75      1629608.53      6902839.47
      1629160.08      6904540.31      1631605.36      6906458.15
      1628356.21      6909848.51      1630147.44      6912988.00
      1628755.06      6914253.38      1629352.98      6915775.99
      1625715.20      6917688.50      1623855.00      6915788.00

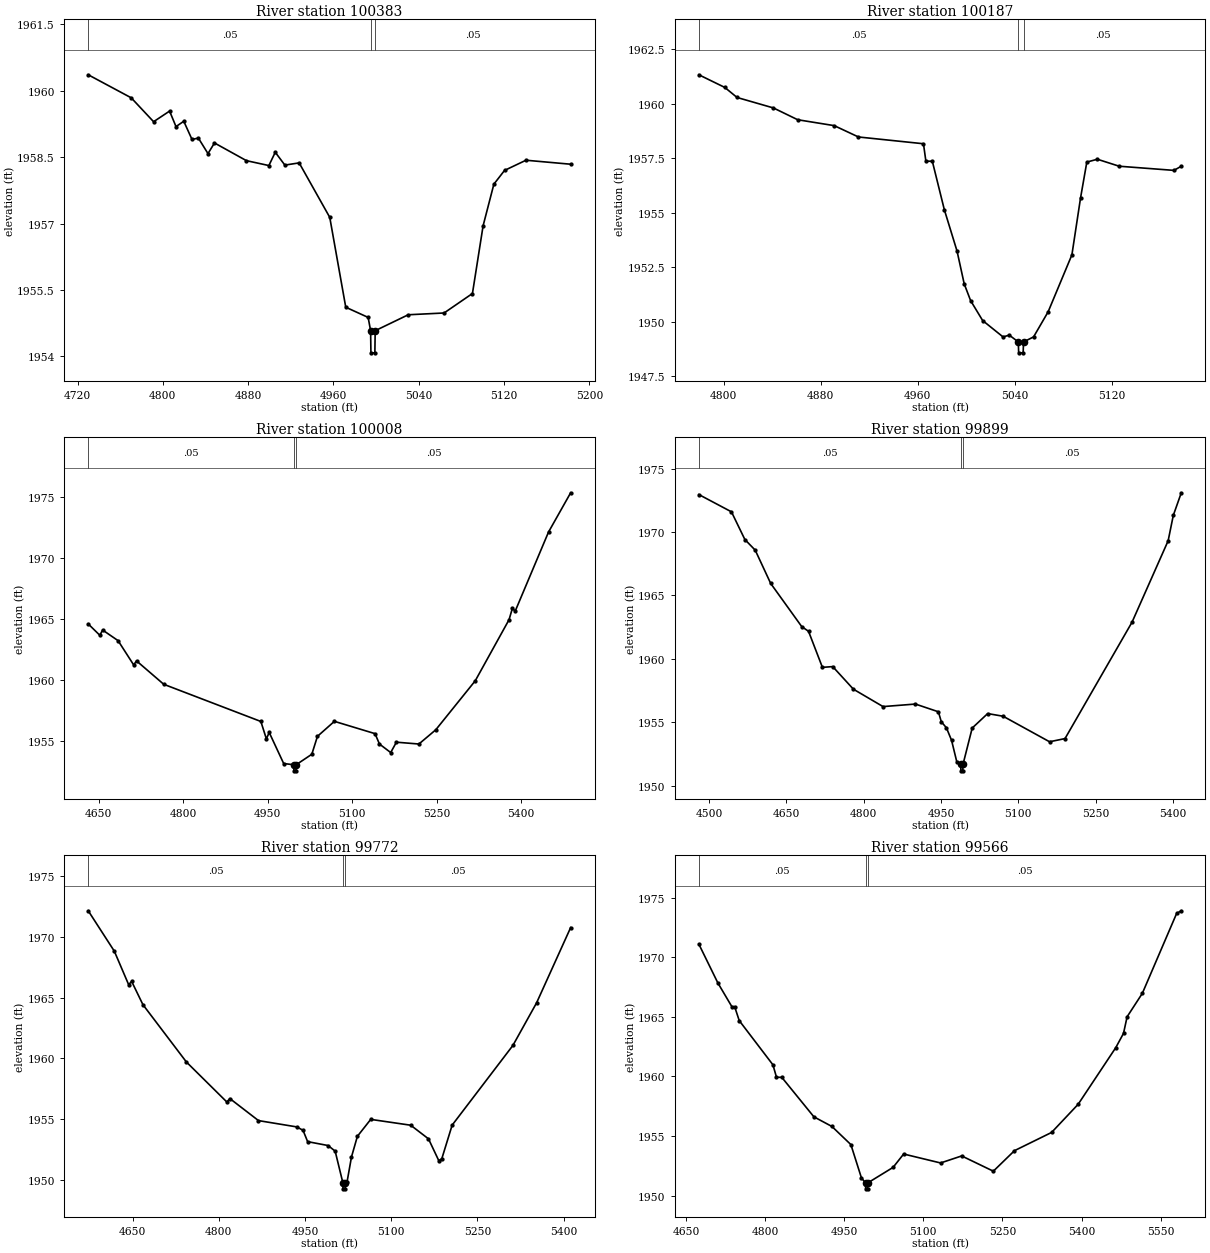
Type RM Length L Ch R = 1,100383,196,196,196
BEGIN DESCRIPTION:
Spring Creek 170.0
END DESCRIPTION:
XS GIS Cut Line= 3
      1662330.55      6864938.07      1662555.00      6864788.00
      1662736.81      6864802.67
#Sta/Elev= 30
  4730.0 1960.36  4770.3 1959.84  4791.3 1959.30  4806.3 1959.54  4812.3 1959.19
  4819.6 1959.31  4827.3 1958.90  4833.3 1958.93  4842.3 1958.58  4848.4 1958.82
  4878.4 1958.42  4899.4 1958.31  4905.4 1958.61  4914.4 1958.32  4927.8 1958.37
  4956.5 1957.14  4971.5 1955.11  4992.5 1954.88  4994.8 1954.58  4995.1 1954.08
  4998.8 1954.08  4999.1 1954.58  5030.1 1954.94  5063.7 1954.98  5090.3 1955.42
  5100.3 1956.95  5110.4 1957.89  5120.4 1958.20  5140.5 1958.43  5182.4 1958.34
#Mann=3,-1,0
  4730.0    0.05       0  4994.8    0.03       0  4999.1    0.05       0
Bank Sta=4994.8,4999.1
Exp/Cntr=0.3,0.1

Type RM Length L Ch R = 1,100187,179,179,179
BEGIN DESCRIPTION:
Mapping XS 2a9d46ff
END DESCRIPTION:
XS GIS Cut Line= 3
      1662343.59      6865003.19      1662531.05      6864992.77
      1662730.83      6864927.91
#Sta/Elev= 30
  4779.6 1961.32  4801.0 1960.74  4811.1 1960.28  4841.1 1959.80  4861.1 1959.26
  4891.2 1958.99  4911.2 1958.47  4964.8 1958.16  4966.8 1957.36  4972.1 1957.36
  4982.0 1955.14  4992.5 1953.24  4998.4 1951.74  5003.7 1950.97  5013.6 1950.06
  5030.4 1949.31  5035.6 1949.39  5043.0 1949.08  5043.3 1948.58  5047.0 1948.58
  5047.3 1949.08  5055.6 1949.31  5067.6 1950.46  5087.2 1953.07  5094.3 1955.67
  5099.5 1957.32  5108.2 1957.45  5126.2 1957.13  5171.3 1956.94  5177.4 1957.13
#Mann=3,-1,0
  4779.6    0.05       0  5043.0    0.03       0  5047.3    0.05       0
Bank Sta=5043,5047.3
Exp/Cntr=0.3,0.1

Type RM Length L Ch R = 1,100008,109,109,109
BEGIN DESCRIPTION:
Mapping XS ac8954bb
END DESCRIPTION:
XS GIS Cut Line= 3
      1662292.77      6865059.02      1662628.66      6865116.31
      1663144.30      6865137.14
#Sta/Elev= 30
  4631.4 1964.60  4652.0 1963.67  4657.0 1964.10  4684.4 1963.23  4712.1 1961.24
  4717.2 1961.57  4765.5 1959.65  4938.0 1956.60  4947.8 1955.17  4952.8 1955.70
  4978.5 1953.15  4996.4 1953.05  4996.7 1952.55  5000.4 1952.55  5000.7 1953.05
  5028.5 1953.91  5038.5 1955.38  5068.6 1956.61  5140.8 1955.60  5148.6 1954.75
  5168.6 1954.05  5178.7 1954.90  5218.7 1954.75  5248.7 1955.92  5318.8 1959.94
  5378.8 1964.95  5384.7 1965.88  5389.7 1965.65  5448.9 1972.14  5488.2 1975.36
#Mann=3,-1,0
  4631.4    0.05       0  4996.4    0.03       0  5000.7    0.05       0
Bank Sta=4996.4,5000.7
Exp/Cntr=0.3,0.1

Type RM Length L Ch R = 1,99899,127,127,127
BEGIN DESCRIPTION:
Mapping XS 8049f6ec
END DESCRIPTION:
XS GIS Cut Line= 3
      1662185.99      6865178.81      1662649.49      6865210.06
      1663120.47      6865217.86
#Sta/Elev= 30
  4480.4 1972.95  4543.6 1971.59  4569.6 1969.41  4589.7 1968.57  4619.7 1965.95
  4679.9 1962.55  4693.1 1962.18  4720.0 1959.34  4740.0 1959.40  4780.1 1957.62
  4837.6 1956.25  4900.4 1956.45  4945.0 1955.84  4950.5 1955.06  4960.5 1954.58
  4970.5 1953.59  4980.5 1951.92  4988.3 1951.69  4988.6 1951.19  4992.3 1951.19
  4992.6 1951.69  5010.5 1954.56  5040.5 1955.70  5070.5 1955.49  5160.5 1953.48
  5190.5 1953.73  5320.5 1962.90  5390.5 1969.31  5400.5 1971.31  5416.0 1973.09
#Mann=3,-1,0
  4480.4    0.05       0  4988.3    0.05       0  4992.6    0.05       0
Bank Sta=4988.3,4992.6
Exp/Cntr=0.3,0.1

Type RM Length L Ch R = 1,99772,206,206,206
BEGIN DESCRIPTION:
Spring Creek 169.0
END DESCRIPTION:
XS GIS Cut Line= 3
      1662305.03      6865487.99      1662705.00      6865338.00
      1663105.02      6865237.99
#Sta/Elev= 30
  4572.7 1972.13  4618.1 1968.81  4643.0 1966.06  4648.3 1966.32  4667.9 1964.41
  4743.5 1959.70  4813.9 1956.41  4819.2 1956.69  4869.0 1954.88  4935.8 1954.36
  4946.5 1954.08  4954.5 1953.15  4990.1 1952.83  5002.4 1952.37  5015.8 1949.77
  5016.1 1949.27  5019.8 1949.27  5020.1 1949.77  5023.1 1949.84  5030.8 1951.89
  5041.1 1953.59  5064.3 1954.98  5133.9 1954.50  5164.8 1953.38  5182.8 1951.58
  5188.0 1951.75  5206.0 1954.51  5311.7 1961.06  5352.9 1964.56  5412.2 1970.75
#Mann=3,-1,0
  4572.7    0.05       0  5015.8    0.05       0  5020.1    0.05       0
Bank Sta=5015.8,5020.1
Exp/Cntr=0.3,0.1

Type RM Length L Ch R = 1,99566,239,239,239
BEGIN DESCRIPTION:
Mapping XS 58112958
END DESCRIPTION:
XS GIS Cut Line= 4
      1662329.23      6865561.61      1662579.18      6865527.76
      1662959.39      6865532.97      1663188.54      6865368.92
#Sta/Elev= 30
  4674.6 1971.09  4710.7 1967.83  4737.4 1965.83  4742.4 1965.85  4751.1 1964.68
  4815.0 1960.97  4821.7 1959.93  4831.8 1959.92  4892.6 1956.61  4926.8 1955.80
  4962.7 1954.28  4982.7 1951.49  4990.5 1951.07  4990.8 1950.57  4994.5 1950.57
  4994.8 1951.07  5042.7 1952.37  5062.7 1953.49  5132.7 1952.74  5172.7 1953.33
  5232.7 1952.05  5272.7 1953.77  5343.1 1955.30  5393.4 1957.66  5464.7 1962.41
  5479.4 1963.61  5486.2 1965.00  5515.0 1966.96  5580.1 1973.67  5588.9 1973.89
#Mann=3,-1,0
  4674.6    0.05       0  4990.5    0.05       0  4994.8    0.05       0
Bank Sta=4990.5,4994.8
Exp/Cntr=0.3,0.1

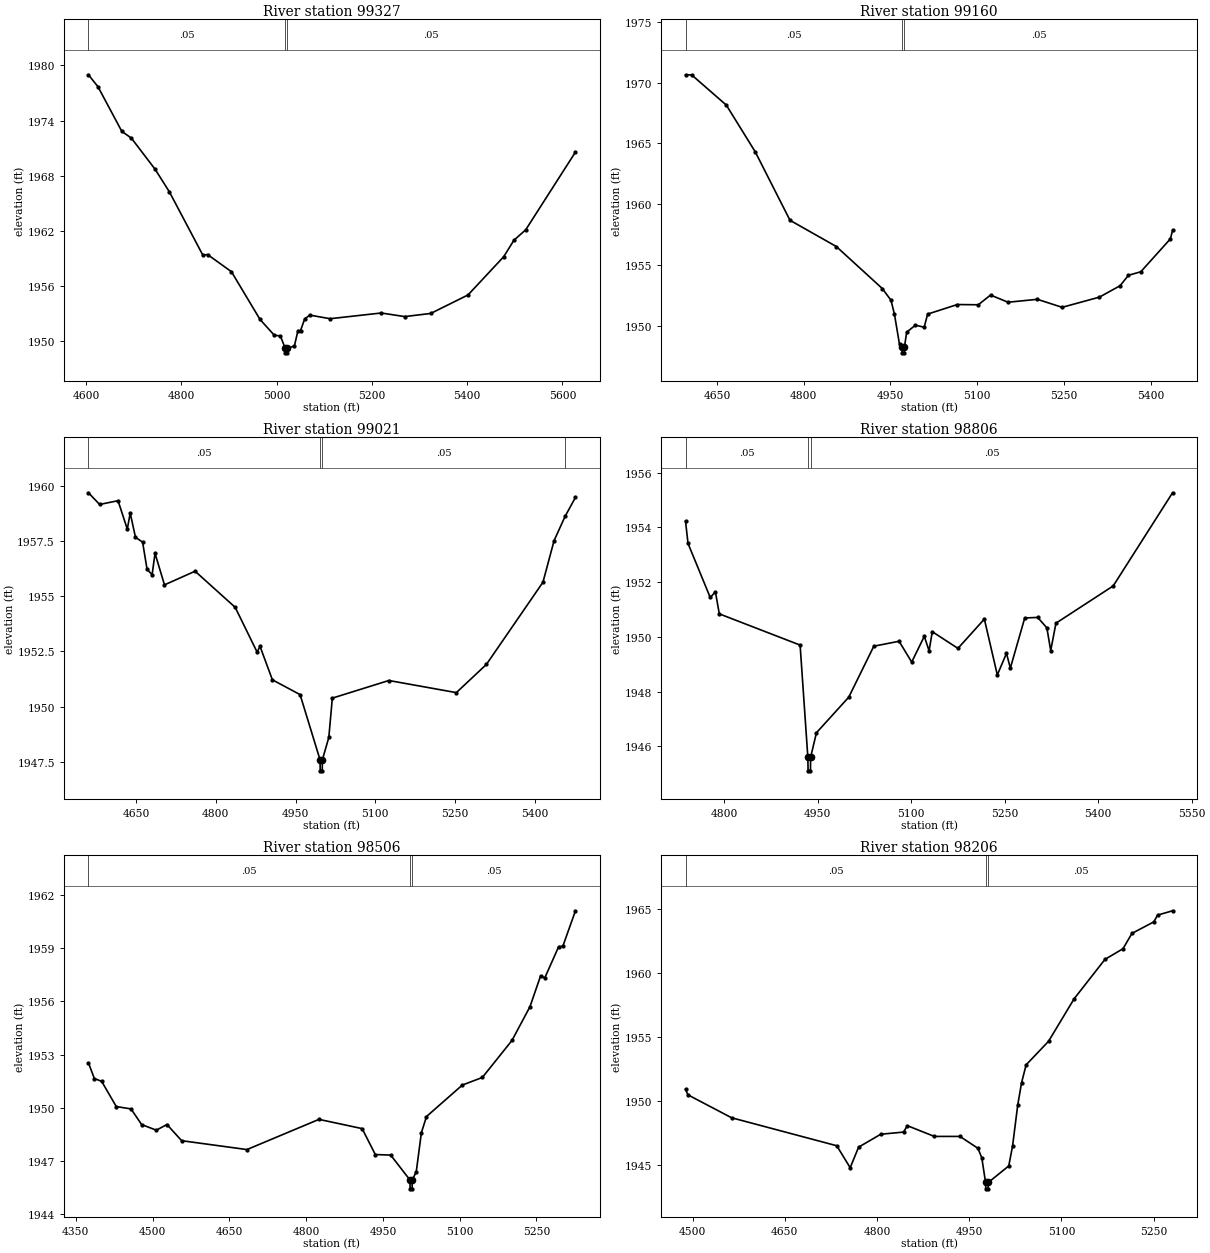
Type RM Length L Ch R = 1,99327,167,167,167
BEGIN DESCRIPTION:
Spring Creek 168.0
END DESCRIPTION:
XS GIS Cut Line= 3
      1662255.01      6865738.00      1662655.00      6865738.00
      1663235.45      6865514.74
#Sta/Elev= 30
  4605.3 1978.97  4625.3 1977.67  4675.3 1972.82  4695.3 1972.09  4745.3 1968.69
  4775.3 1966.23  4845.3 1959.37  4855.3 1959.43  4905.3 1957.57  4965.3 1952.38
  4995.3 1950.66  5008.0 1950.59  5018.1 1949.25  5018.4 1948.75  5022.2 1948.75
  5022.5 1949.25  5037.4 1949.49  5044.9 1951.16  5050.3 1951.17  5058.9 1952.42
  5069.6 1952.85  5112.4 1952.46  5219.6 1953.08  5268.9 1952.69  5323.5 1953.03
  5401.7 1955.04  5476.7 1959.20  5498.1 1960.99  5522.8 1962.12  5627.2 1970.57
#Mann=3,-1,0
  4605.3    0.05       0  5018.1    0.05       0  5022.5    0.05       0
Bank Sta=5018.1,5022.5
Exp/Cntr=0.3,0.1

Type RM Length L Ch R = 1,99160,139,139,139
BEGIN DESCRIPTION:
Mapping XS e46230aa
END DESCRIPTION:
XS GIS Cut Line= 3
      1662334.41      6865920.99      1662646.89      6865907.97
      1663091.07      6865619.65
#Sta/Elev= 30
  4595.7 1970.66  4606.3 1970.65  4666.3 1968.16  4716.4 1964.30  4776.4 1958.67
  4856.5 1956.51  4936.0 1953.05  4951.1 1952.08  4957.1 1950.91  4965.8 1948.44
  4970.0 1948.25  4970.3 1947.75  4974.1 1947.75  4974.4 1948.25  4978.2 1949.45
  4993.3 1950.03  5008.5 1949.86  5014.4 1950.94  5065.8 1951.73  5102.1 1951.71
  5123.2 1952.51  5153.5 1951.92  5204.2 1952.16  5247.1 1951.50  5311.5 1952.34
  5347.3 1953.28  5361.8 1954.14  5383.1 1954.43  5434.3 1957.14  5438.0 1957.83
#Mann=3,-1,0
  4595.7    0.05       0  4970.0    0.05       0  4974.4    0.05       0
Bank Sta=4970,4974.4
Exp/Cntr=0.3,0.1

Type RM Length L Ch R = 1,99021,215,215,215
BEGIN DESCRIPTION:
Spring Creek 167.0
END DESCRIPTION:
XS GIS Cut Line= 3
      1662404.02      6866142.87      1662818.11      6865960.57
      1663138.41      6865624.64
#Sta/Elev= 30
  4560.2 1959.70  4581.2 1959.17  4615.9 1959.34  4633.3 1958.05  4638.8 1958.78
  4648.7 1957.68  4662.1 1957.46  4670.5 1956.23  4680.0 1955.98  4685.5 1956.95
  4703.3 1955.52  4760.9 1956.14  4836.4 1954.50  4877.6 1952.47  4883.1 1952.73
  4906.4 1951.21  4958.5 1950.54  4996.1 1947.58  4996.4 1947.08  5000.2 1947.08
  5000.5 1947.58  5012.6 1948.60  5019.2 1950.38  5125.6 1951.18  5252.6 1950.63
  5309.2 1951.91  5415.6 1955.64  5436.6 1957.53  5457.3 1958.63  5476.8 1959.49
#Mann=4,-1,0
  4560.2    0.05       0  4996.1    0.05       0  5000.5    0.05       0
  5457.3    0.12       0
Bank Sta=4996.1,5000.5
Exp/Cntr=0.3,0.1

Type RM Length L Ch R = 1,98806,300,300,300
BEGIN DESCRIPTION:
Mapping XS a484f3ae
END DESCRIPTION:
XS GIS Cut Line= 5
      1662789.25      6866358.49      1662916.35      6866184.86
      1662916.35      6866109.68      1662893.08      6865964.69
      1663097.13      6865687.25
#Sta/Elev= 30
  4737.7 1954.22  4741.7 1953.41  4777.3 1951.44  4785.7 1951.64  4791.9 1950.84
  4921.6 1949.70  4934.0 1945.61  4934.4 1945.11  4938.2 1945.11  4938.5 1945.61
  4947.8 1946.50  4999.7 1947.80  5039.9 1949.66  5080.4 1949.84  5100.7 1949.08
  5120.9 1950.02  5128.6 1949.49  5133.7 1950.19  5174.9 1949.58  5217.3 1950.65
  5238.1 1948.61  5252.8 1949.40  5259.0 1948.86  5282.1 1950.69  5302.9 1950.71
  5317.6 1950.33  5323.8 1949.50  5332.2 1950.50  5424.1 1951.86  5519.3 1955.26
#Mann=3,-1,0
  4737.7    0.05       0  4934.0    0.05       0  4938.5    0.05       0
Bank Sta=4934,4938.5
Exp/Cntr=0.3,0.1

Type RM Length L Ch R = 1,98506,300,300,300
BEGIN DESCRIPTION:
Mapping XS 45593ef0
END DESCRIPTION:
XS GIS Cut Line= 4
      1662836.24      6866486.10      1663064.92      6866209.92
      1663054.18      6865826.86      1663183.79      6865661.73
#Sta/Elev= 30
  4374.6 1952.53  4386.1 1951.65  4400.4 1951.49  4429.0 1950.07  4457.7 1949.94
  4478.5 1949.06  4507.2 1948.74  4528.0 1949.06  4556.7 1948.15  4684.3 1947.65
  4825.1 1949.35  4909.4 1948.83  4935.2 1947.37  4965.2 1947.34  5002.9 1945.94
  5003.2 1945.44  5007.1 1945.44  5007.4 1945.94  5015.2 1946.40  5025.2 1948.60
  5035.2 1949.51  5105.2 1951.28  5144.4 1951.71  5202.2 1953.79  5237.4 1955.69
  5258.2 1957.43  5266.3 1957.31  5293.5 1959.07  5301.6 1959.09  5326.3 1961.09
#Mann=3,-1,0
  4374.6    0.05       0  5002.9    0.03       0  5007.4    0.05       0
Bank Sta=5002.9,5007.4
Exp/Cntr=0.3,0.1

Type RM Length L Ch R = 1,98206,247,247,247
BEGIN DESCRIPTION:
Mapping XS 4763441c
END DESCRIPTION:
XS GIS Cut Line= 2
      1662859.83      6866457.61      1663496.34      6865986.15
#Sta/Elev= 30
  4488.6 1950.90  4492.6 1950.47  4563.5 1948.68  4734.6 1946.49  4756.4 1944.77
  4770.1 1946.38  4806.1 1947.39  4843.2 1947.56  4849.4 1948.06  4893.3 1947.22
  4935.0 1947.22  4964.2 1946.29  4970.5 1945.54  4976.6 1943.62  4976.9 1943.12
  4980.8 1943.12  4981.1 1943.62  5014.3 1944.91  5020.5 1946.46  5028.9 1949.67
  5035.2 1951.43  5042.6 1952.82  5079.0 1954.66  5120.7 1957.99  5170.8 1961.07
  5200.1 1961.90  5214.7 1963.10  5250.2 1964.00  5256.4 1964.53  5280.7 1964.87
#Mann=3,-1,0
  4488.6    0.05       0  4976.6    0.05       0  4981.1    0.05       0
Bank Sta=4976.6,4981.1
Exp/Cntr=0.3,0.1

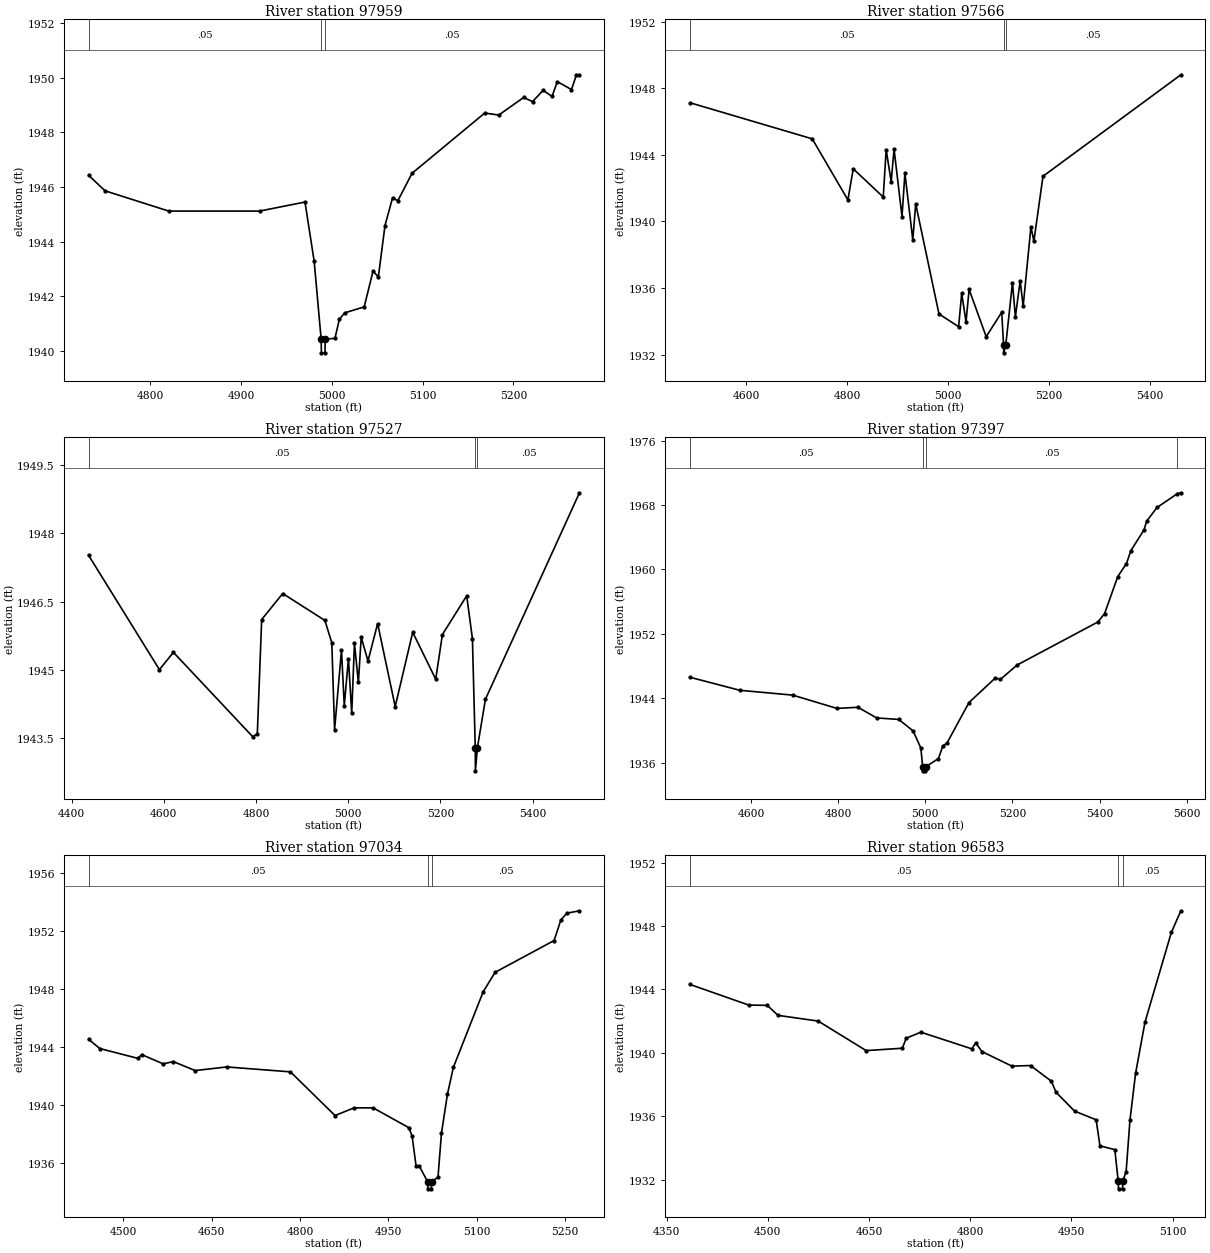
Type RM Length L Ch R = 1,97959,393,393,393
BEGIN DESCRIPTION:
Spring Creek 166.0
END DESCRIPTION:
XS GIS Cut Line= 3
      1663036.82      6866400.68      1663305.00      6866388.00
      1663539.44      6866249.65
#Sta/Elev= 30
  4732.0 1946.43  4750.2 1945.86  4820.3 1945.12  4920.4 1945.12  4970.4 1945.45
  4980.5 1943.29  4988.2 1940.44  4988.5 1939.94  4992.4 1939.94  4992.7 1940.44
  5003.4 1940.47  5008.3 1941.17  5014.1 1941.40  5035.6 1941.62  5045.4 1942.93
  5051.2 1942.71  5058.5 1944.59  5066.8 1945.60  5072.7 1945.50  5088.3 1946.50
  5168.3 1948.70  5183.9 1948.63  5211.2 1949.27  5221.0 1949.12  5232.7 1949.53
  5242.5 1949.31  5248.3 1949.85  5263.9 1949.56  5269.4 1950.10  5272.7 1950.10
#Mann=3,-1,0
  4732.0    0.05       0  4988.2    0.05       0  4992.7    0.05       0
Bank Sta=4988.2,4992.7
Exp/Cntr=0.3,0.1

Type RM Length L Ch R = 1,97566,39,39,39
BEGIN DESCRIPTION:
Mapping XS 4def79ab
END DESCRIPTION:
XS GIS Cut Line= 6
      1662984.36      6866618.04      1663426.50      6866721.86
      1663476.62      6866707.54      1663508.84      6866662.79
      1663439.03      6866550.02      1663519.58      6866288.68
#Sta/Elev= 30
  4488.5 1947.13  4731.1 1944.96  4801.8 1941.29  4812.4 1943.16  4871.9 1941.46
  4877.7 1944.30  4887.6 1942.39  4893.4 1944.34  4909.1 1940.28  4914.9 1942.89
  4930.5 1938.89  4936.3 1941.05  4982.4 1934.44  5021.4 1933.67  5027.5 1935.67
  5036.1 1933.96  5042.2 1935.91  5076.1 1933.07  5106.9 1934.54  5110.5 1932.60
  5110.8 1932.10  5115.0 1932.60  5128.2 1936.31  5134.0 1934.26  5143.5 1936.43
  5149.4 1934.89  5164.8 1939.67  5170.7 1938.81  5188.7 1942.71  5462.2 1948.81
#Mann=3,-1,0
  4488.5    0.05       0  5110.5    0.05       0  5115.0    0.05       0
Bank Sta=5110.5,5115
Exp/Cntr=0.3,0.1

Type RM Length L Ch R = 1,97527,130,130,130
BEGIN DESCRIPTION:
Mapping XS f337fdef
END DESCRIPTION:
XS GIS Cut Line= 6
      1662962.85      6866673.53      1663447.98      6866771.98
      1663507.05      6866732.60      1663548.22      6866623.41
      1663474.83      6866526.75      1663546.42      6866283.35
#Sta/Elev= 30
  4436.6 1947.52  4590.4 1945.01  4620.7 1945.39  4792.6 1943.54  4802.7 1943.60
  4812.2 1946.11  4857.8 1946.68  4949.3 1946.09  4964.3 1945.60  4970.3 1943.69
  4985.3 1945.44  4991.3 1944.22  5000.4 1945.25  5007.5 1944.05  5013.4 1945.59
  5021.9 1944.73  5028.1 1945.72  5042.8 1945.20  5063.7 1946.02  5101.8 1944.20
  5139.8 1945.83  5189.7 1944.80  5204.2 1945.78  5256.9 1946.63  5269.3 1945.69
  5275.5 1943.29  5275.8 1942.79  5280.0 1943.29  5297.5 1944.36  5501.5 1948.89
#Mann=3,-1,0
  4436.6    0.05       0  5275.5    0.05       0  5280.0    0.05       0
Bank Sta=5275.5,5280
Exp/Cntr=0.3,0.1

Type RM Length L Ch R = 1,97397,363,363,363
BEGIN DESCRIPTION:
Spring Creek 165.0
END DESCRIPTION:
XS GIS Cut Line= 3
      1662982.20      6866739.22      1663515.05      6866828.02
      1664099.36      6866879.84
#Sta/Elev= 30
  4459.8 1946.62  4574.2 1945.00  4695.8 1944.40  4797.2 1942.75  4845.3 1942.89
  4888.4 1941.57  4939.1 1941.38  4972.0 1939.96  4989.8 1937.83  4994.0 1935.50
  4994.5 1935.00  5000.3 1935.00  5000.8 1935.50  5030.1 1936.52  5040.1 1938.06
  5050.1 1938.48  5100.3 1943.48  5160.6 1946.52  5172.6 1946.36  5210.8 1948.14
  5396.2 1953.48  5411.6 1954.53  5441.7 1959.11  5461.8 1960.74  5471.8 1962.33
  5501.9 1964.91  5508.1 1966.00  5532.0 1967.70  5578.7 1969.41  5586.6 1969.52
#Mann=4,-1,0
  4459.8    0.05       0  4994.0    0.03       0  5000.8    0.05       0
  5578.7    0.12       0
Bank Sta=4994,5000.8
Exp/Cntr=0.3,0.1

Type RM Length L Ch R = 1,97034,451,451,451
BEGIN DESCRIPTION:
Spring Creek 164.0
END DESCRIPTION:
XS GIS Cut Line= 3
      1662987.40      6866978.81      1663505.00      6867188.00
      1663776.48      6867228.80
#Sta/Elev= 30
  4441.3 1944.52  4460.3 1943.88  4525.0 1943.20  4531.5 1943.46  4568.1 1942.82
  4585.1 1942.98  4622.1 1942.36  4676.0 1942.61  4783.9 1942.27  4859.4 1939.26
  4891.7 1939.79  4924.1 1939.79  4984.8 1938.42  4990.2 1937.84  4996.9 1935.80
  5002.1 1935.80  5016.4 1934.71  5016.9 1934.21  5022.8 1934.21  5023.3 1934.71
  5034.1 1935.01  5040.0 1938.04  5050.1 1940.72  5060.2 1942.58  5110.8 1947.79
  5131.0 1949.13  5231.1 1951.32  5242.3 1952.71  5252.4 1953.20  5274.1 1953.37
#Mann=3,-1,0
  4441.3    0.05       0  5016.4    0.03       0  5023.3    0.05       0
Bank Sta=5016.4,5023.3
Exp/Cntr=0.3,0.1

Type RM Length L Ch R = 1,96583,203,203,203
BEGIN DESCRIPTION:
Spring Creek 163.0
END DESCRIPTION:
XS GIS Cut Line= 3
      1662956.14      6866999.64      1663255.00      6867538.00
      1663355.04      6867588.02
#Sta/Elev= 30
  4384.6 1944.32  4471.7 1943.02  4499.2 1943.00  4515.2 1942.37  4574.7 1942.01
  4645.8 1940.15  4699.4 1940.30  4705.1 1940.93  4726.9 1941.31  4802.4 1940.26
  4808.1 1940.64  4817.3 1940.09  4861.9 1939.17  4889.4 1939.21  4920.3 1938.22
  4927.1 1937.53  4954.6 1936.34  4986.6 1935.79  4992.3 1934.15  5014.3 1933.91
  5019.3 1931.94  5019.8 1931.44  5025.7 1931.44  5026.2 1931.94  5031.1 1932.53
  5036.7 1935.75  5045.1 1938.72  5059.0 1941.94  5098.2 1947.61  5112.2 1948.96
#Mann=3,-1,0
  4384.6    0.05       0  5019.3    0.03       0  5026.2    0.05       0
Bank Sta=5019.3,5026.2
Exp/Cntr=0.3,0.1

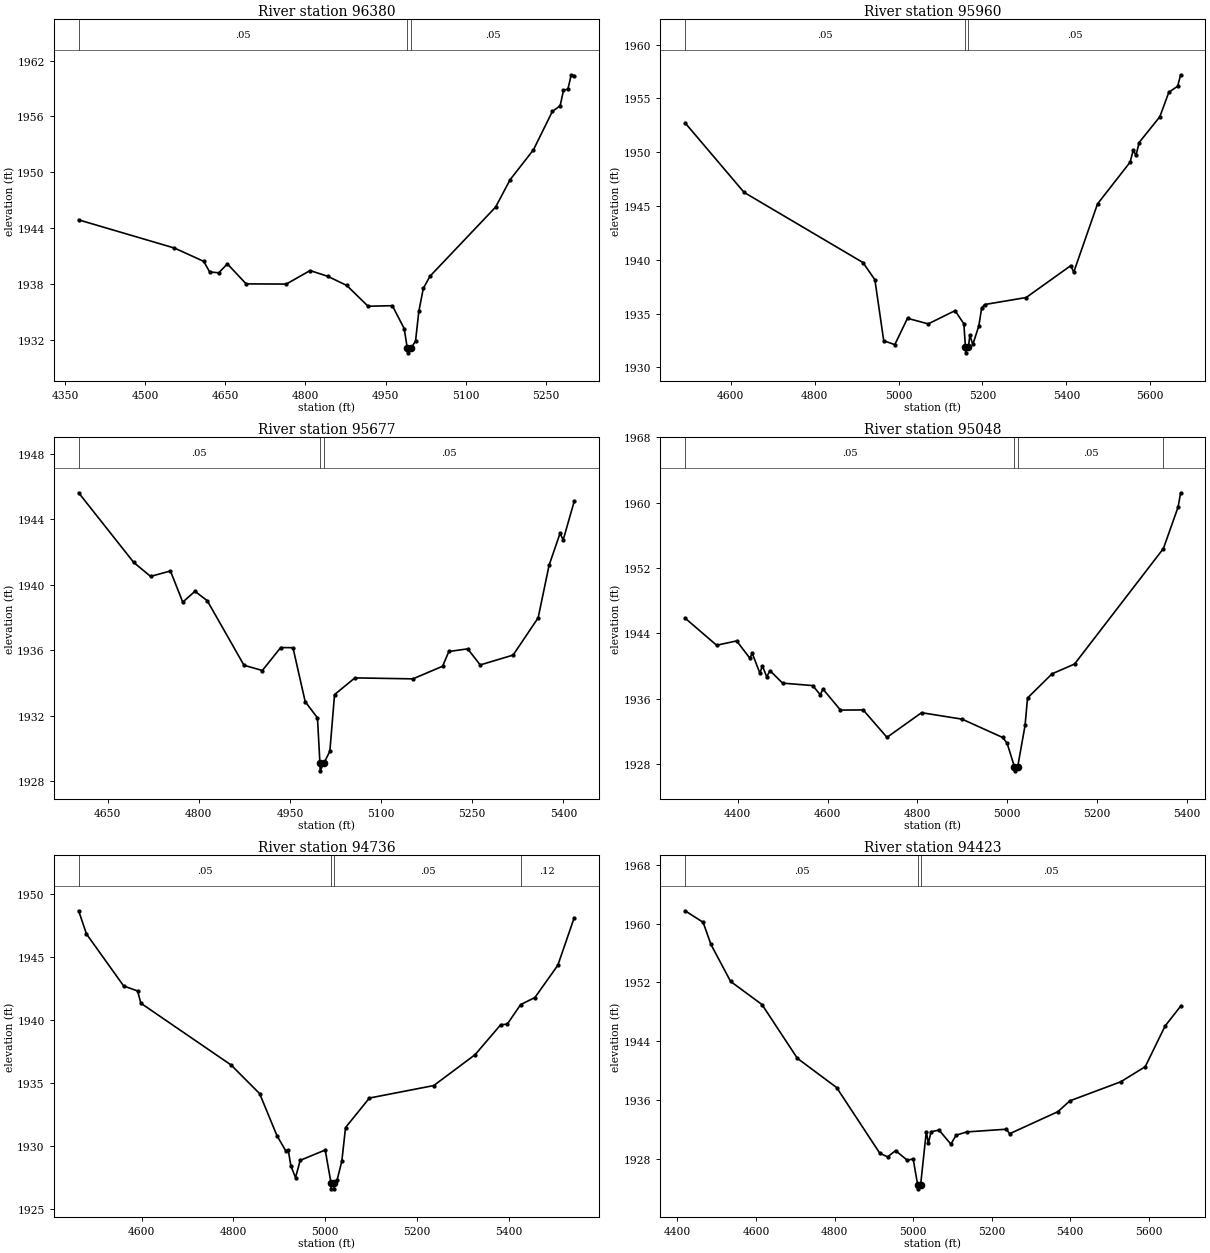
Type RM Length L Ch R = 1,96380,420,420,420
BEGIN DESCRIPTION:
Mapping XS 969e5686
END DESCRIPTION:
XS GIS Cut Line= 3
      1662828.53      6867085.59      1663091.55      6867648.07
      1663275.55      6867894.27
#Sta/Elev= 30
  4375.1 1944.90  4554.4 1941.88  4609.4 1940.45  4620.6 1939.31  4637.7 1939.22
  4653.7 1940.18  4688.9 1938.03  4764.1 1938.01  4808.7 1939.46  4841.4 1938.85
  4877.2 1937.87  4917.4 1935.63  4962.8 1935.69  4984.9 1933.24  4990.8 1931.13
  4991.3 1930.63  4997.7 1931.13  5006.2 1931.88  5012.4 1935.08  5020.8 1937.55
  5033.4 1938.86  5156.2 1946.27  5183.3 1949.20  5227.1 1952.42  5262.5 1956.53
  5277.1 1957.14  5283.4 1958.79  5291.7 1958.95  5298.0 1960.47  5303.4 1960.39
#Mann=3,-1,0
  4375.1    0.05       0  4990.8    0.03       0  4997.7    0.05       0
Bank Sta=4990.8,4997.7
Exp/Cntr=0.3,0.1

Type RM Length L Ch R = 1,95960,283,283,283
BEGIN DESCRIPTION:
Spring Creek 162.0
END DESCRIPTION:
XS GIS Cut Line= 3
      1662385.85      6867288.73      1662758.21      6867622.03
      1663255.02      6868088.02
#Sta/Elev= 30
  4491.4 1952.72  4632.0 1946.26  4915.3 1939.74  4943.7 1938.14  4964.7 1932.48
  4991.1 1932.11  5021.4 1934.56  5070.8 1934.04  5134.7 1935.27  5155.7 1934.05
  5159.5 1931.85  5160.0 1931.35  5166.5 1931.85  5169.9 1932.97  5177.2 1932.14
  5191.4 1933.86  5198.2 1935.53  5205.5 1935.84  5304.2 1936.49  5410.7 1939.46
  5417.5 1938.84  5474.2 1945.19  5551.9 1949.07  5559.2 1950.17  5566.0 1949.70
  5573.3 1950.89  5622.7 1953.29  5644.2 1955.57  5665.2 1956.13  5672.3 1957.19
#Mann=3,-1,0
  4491.4    0.05       0  5159.5    0.03       0  5166.5    0.05       0
Bank Sta=5159.5,5166.5
Exp/Cntr=0.3,0.1

Type RM Length L Ch R = 1,95677,629,629,629
BEGIN DESCRIPTION:
Spring Creek 161.0
END DESCRIPTION:
XS GIS Cut Line= 3
      1662305.04      6867838.00      1662705.00      6867888.00
      1663105.01      6867988.00
#Sta/Elev= 30
  4602.3 1945.61  4693.0 1941.36  4720.7 1940.51  4753.4 1940.84  4773.6 1938.94
  4793.7 1939.60  4813.9 1939.03  4874.4 1935.09  4904.6 1934.77  4934.8 1936.17
  4955.0 1936.16  4975.1 1932.87  4995.3 1931.88  4999.3 1929.15  4999.8 1928.65
  5006.4 1929.15  5015.7 1929.85  5023.4 1933.30  5056.9 1934.32  5152.3 1934.26
  5201.2 1935.03  5211.5 1935.93  5242.5 1936.09  5263.1 1935.11  5317.2 1935.71
  5358.4 1937.98  5376.5 1941.20  5394.5 1943.14  5399.6 1942.73  5417.7 1945.08
#Mann=3,-1,0
  4602.3    0.05       0  4999.3    0.05       0  5006.4    0.05       0
Bank Sta=4999.3,5006.4
Exp/Cntr=0.3,0.1

Type RM Length L Ch R = 1,95048,312,312,312
BEGIN DESCRIPTION:
Mapping XS 25b19395
END DESCRIPTION:
XS GIS Cut Line= 3
      1662292.06      6868507.45      1662755.61      6868278.28
      1663340.77      6868241.87
#Sta/Elev= 30
  4282.9 1945.85  4353.1 1942.53  4397.7 1943.06  4427.0 1940.95  4432.5 1941.54
  4449.4 1939.11  4455.0 1940.01  4464.7 1938.65  4471.8 1939.43  4499.9 1937.89
  4567.2 1937.59  4584.0 1936.45  4589.6 1937.18  4628.9 1934.59  4679.4 1934.61
  4732.4 1931.25  4809.4 1934.27  4899.6 1933.48  4989.8 1931.24  4999.8 1930.55
  5016.2 1927.65  5016.7 1927.15  5023.5 1927.65  5039.9 1932.72  5045.4 1936.07
  5100.0 1939.03  5150.1 1940.23  5347.9 1954.37  5380.5 1959.43  5386.3 1961.20
#Mann=4,-1,0
  4282.9    0.05       0  5016.2    0.03       0  5023.5    0.05       0
  5347.9    0.12       0
Bank Sta=5016.2,5023.5
Exp/Cntr=0.3,0.1

Type RM Length L Ch R = 1,94736,313,313,313
BEGIN DESCRIPTION:
Spring Creek 160.0
END DESCRIPTION:
XS GIS Cut Line= 3
      1662318.14      6868624.63      1662848.86      6868540.17
      1663390.49      6868572.52
#Sta/Elev= 30
  4462.6 1948.65  4479.7 1946.81  4560.7 1942.69  4591.1 1942.29  4598.2 1941.32
  4794.9 1936.42  4857.1 1934.15  4894.8 1930.82  4914.2 1929.60  4919.3 1929.70
  4925.2 1928.42  4935.3 1927.49  4945.5 1928.86  5000.0 1929.68  5012.5 1927.10
  5013.0 1926.60  5019.3 1926.60  5019.8 1927.10  5026.2 1927.34  5036.2 1928.79
  5044.3 1931.46  5096.3 1933.80  5236.6 1934.79  5326.7 1937.24  5382.4 1939.61
  5396.8 1939.66  5425.9 1941.21  5457.0 1941.77  5507.0 1944.33  5542.6 1948.09
#Mann=4,-1,0
  4462.6    0.05       0  5012.5    0.05       0  5019.8    0.05       0
  5425.9    0.12       0
Bank Sta=5012.5,5019.8
Exp/Cntr=0.3,0.1

Type RM Length L Ch R = 1,94423,478,478,478
BEGIN DESCRIPTION:
Mapping XS a99b9a56
END DESCRIPTION:
XS GIS Cut Line= 3
      1662219.12      6868825.15      1662799.88      6868838.17
      1663474.33      6868741.82
#Sta/Elev= 30
  4419.4 1961.75  4465.3 1960.18  4485.3 1957.16  4535.3 1952.13  4615.3 1948.98
  4705.4 1941.66  4805.4 1937.68  4915.4 1928.73  4935.4 1928.24  4955.4 1929.10
  4985.4 1927.78  5000.3 1927.97  5011.9 1924.39  5012.4 1923.89  5019.2 1924.39
  5033.8 1931.69  5038.9 1930.09  5045.9 1931.66  5066.1 1931.89  5096.4 1929.98
  5109.6 1931.19  5136.8 1931.64  5237.8 1932.01  5245.9 1931.39  5369.1 1934.40
  5399.4 1935.87  5528.8 1938.46  5591.4 1940.52  5641.9 1946.05  5681.6 1948.76
#Mann=3,-1,0
  4419.4    0.05       0  5011.9    0.03       0  5019.2    0.05       0
Bank Sta=5011.9,5019.2
Exp/Cntr=0.3,0.1

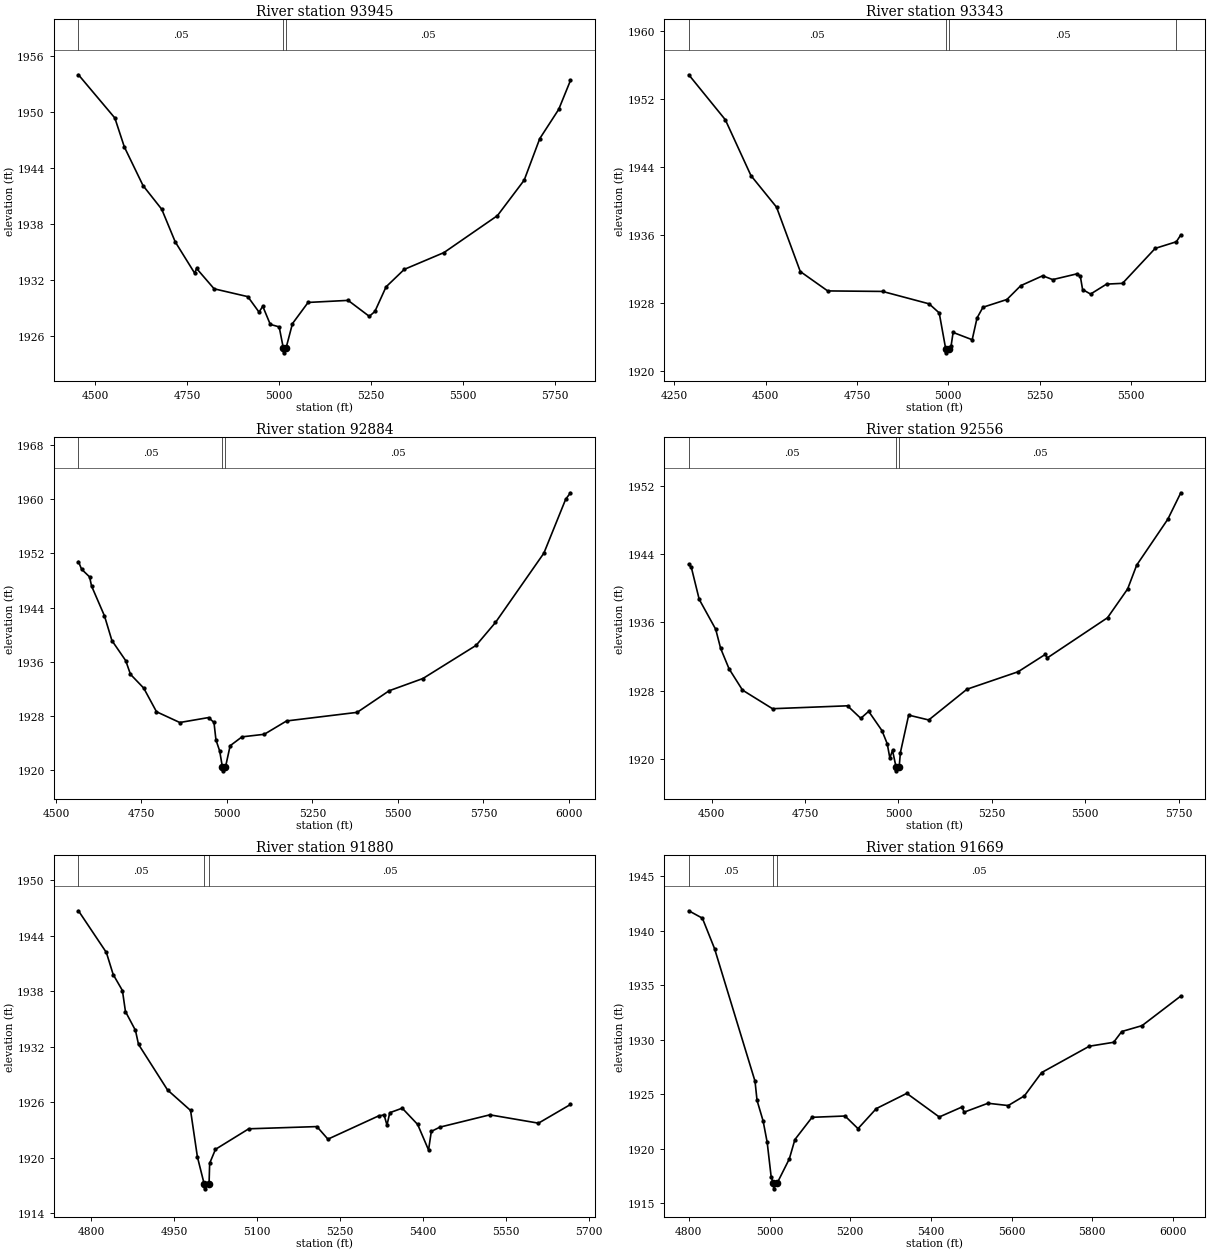
Type RM Length L Ch R = 1,93945,602,602,602
BEGIN DESCRIPTION:
Spring Creek 159.0
END DESCRIPTION:
XS GIS Cut Line= 3
      1662362.37      6869280.88      1662898.84      6869181.92
      1663565.46      6868754.87
#Sta/Elev= 30
  4455.0 1953.99  4553.9 1949.36  4579.7 1946.26  4630.5 1942.12  4681.4 1939.58
  4718.0 1936.09  4770.9 1932.73  4776.0 1933.24  4823.7 1931.06  4915.3 1930.22
  4945.8 1928.56  4955.9 1929.19  4976.3 1927.25  5000.5 1926.98  5011.8 1924.70
  5012.3 1924.20  5019.1 1924.70  5036.6 1927.33  5079.1 1929.60  5187.9 1929.82
  5245.4 1928.11  5260.6 1928.63  5291.0 1931.27  5340.4 1933.14  5448.3 1934.94
  5593.7 1938.90  5666.4 1942.70  5708.7 1947.15  5760.3 1950.29  5792.2 1953.39
#Mann=3,-1,0
  4455.0    0.05       0  5011.8    0.03       0  5019.1    0.05       0
Bank Sta=5011.8,5019.1
Exp/Cntr=0.3,0.1

Type RM Length L Ch R = 1,93343,459,459,459
BEGIN DESCRIPTION:
Spring Creek 158.0
END DESCRIPTION:
XS GIS Cut Line= 3
      1662354.97      6869338.00      1662921.68      6869328.71
      1663606.60      6869701.12
#Sta/Elev= 30
  4290.0 1954.85  4390.0 1949.56  4460.1 1943.00  4530.1 1939.29  4595.1 1931.72
  4670.1 1929.44  4820.1 1929.38  4947.7 1927.92  4975.3 1926.85  4992.9 1922.66
  4993.4 1922.16  5001.5 1922.66  5007.6 1922.92  5013.3 1924.56  5065.5 1923.70
  5078.8 1926.26  5095.0 1927.52  5160.5 1928.43  5198.5 1930.06  5258.4 1931.22
  5285.9 1930.77  5351.5 1931.44  5361.4 1931.17  5367.6 1929.60  5389.5 1929.07
  5433.2 1930.24  5476.9 1930.33  5566.3 1934.44  5624.2 1935.22  5636.4 1936.03
#Mann=4,-1,0
  4290.0    0.05       0  4992.9    0.03       0  5001.5    0.05       0
  5624.2    0.12       0
Bank Sta=4992.9,5001.5
Exp/Cntr=0.3,0.1

Type RM Length L Ch R = 1,92884,328,328,328
BEGIN DESCRIPTION:
Spring Creek 157.0
END DESCRIPTION:
XS GIS Cut Line= 3
      1662405.01      6869588.00      1663164.46      6869911.09
      1663605.02      6870338.02
#Sta/Elev= 30
  4565.8 1950.78  4574.9 1949.66  4598.4 1948.52  4604.0 1947.19  4641.9 1942.76
  4663.6 1939.12  4704.0 1936.15  4717.9 1934.13  4756.7 1932.09  4794.0 1928.60
  4862.1 1927.01  4946.1 1927.74  4962.1 1927.02  4967.9 1924.43  4978.8 1922.80
  4986.9 1920.37  4987.4 1919.87  4995.5 1920.37  5009.4 1923.58  5044.0 1924.89
  5109.2 1925.27  5174.4 1927.24  5380.8 1928.51  5474.3 1931.70  5573.1 1933.51
  5728.7 1938.41  5785.3 1941.79  5926.8 1952.03  5990.5 1959.99  6004.6 1960.95
#Mann=3,-1,0
  4565.8    0.05       0  4986.9    0.03       0  4995.5    0.05       0
Bank Sta=4986.9,4995.5
Exp/Cntr=0.3,0.1

Type RM Length L Ch R = 1,92556,676,676,676
BEGIN DESCRIPTION:
Spring Creek 156.0
END DESCRIPTION:
XS GIS Cut Line= 4
      1662465.97      6869637.78      1662676.02      6869958.92
      1662794.07      6870082.18      1663501.18      6870366.41
#Sta/Elev= 30
  4438.9 1942.79  4445.7 1942.44  4466.8 1938.69  4510.9 1935.19  4524.1 1932.95
  4546.7 1930.55  4582.6 1928.06  4662.9 1925.88  4863.6 1926.22  4899.1 1924.75
  4920.2 1925.57  4955.7 1923.32  4969.9 1921.77  4976.8 1920.11  4984.0 1920.99
  4993.2 1919.10  4993.7 1918.60  5001.9 1919.10  5005.1 1920.74  5027.2 1925.13
  5080.9 1924.56  5183.1 1928.16  5320.1 1930.21  5392.7 1932.24  5398.1 1931.83
  5559.3 1936.54  5613.1 1939.91  5637.3 1942.70  5720.6 1948.08  5755.4 1951.18
#Mann=3,-1,0
  4438.9    0.05       0  4993.2    0.03       0  5001.9    0.05       0
Bank Sta=4993.2,5001.9
Exp/Cntr=0.3,0.1

Type RM Length L Ch R = 1,91880,211,211,211
BEGIN DESCRIPTION:
Mapping XS 22cb5bca
END DESCRIPTION:
XS GIS Cut Line= 4
      1662238.50      6869910.28      1662410.39      6870311.35
      1662554.49      6870337.39      1662860.01      6870368.64
#Sta/Elev= 30
  4776.5 1946.72  4827.0 1942.21  4839.3 1939.83  4856.0 1938.10  4861.5 1935.83
  4879.6 1933.79  4885.1 1932.28  4937.6 1927.35  4979.3 1925.13  4991.6 1920.12
  5004.0 1917.16  5004.5 1916.66  5012.7 1917.16  5013.8 1919.42  5024.3 1920.93
  5084.5 1923.15  5207.8 1923.39  5227.7 1922.03  5319.2 1924.54  5329.3 1924.65
  5334.5 1923.55  5339.6 1924.89  5362.1 1925.38  5390.0 1923.62  5409.7 1920.86
  5414.7 1922.87  5430.2 1923.33  5520.6 1924.66  5608.5 1923.76  5666.4 1925.78
#Mann=3,-1,0
  4776.5    0.05       0  5004.0    0.05       0  5012.7    0.05       0
Bank Sta=5004,5012.7
Exp/Cntr=0.3,0.1

Type RM Length L Ch R = 1,91669,77,77,77
BEGIN DESCRIPTION:
Mapping XS fc5533b3
END DESCRIPTION:
XS GIS Cut Line= 4
      1662011.39      6870269.21      1662259.77      6870289.51
      1662552.75      6870349.54      1663220.58      6870418.93
#Sta/Elev= 30
  4799.9 1941.85  4833.6 1941.17  4863.7 1938.38  4964.1 1926.19  4969.1 1924.43
  4984.1 1922.55  4994.2 1920.59  5004.2 1917.38  5009.8 1916.81  5010.3 1916.31
  5018.6 1916.81  5049.1 1919.06  5063.0 1920.84  5105.5 1922.88  5187.2 1923.00
  5219.4 1921.84  5264.7 1923.68  5340.3 1925.08  5420.8 1922.91  5477.3 1923.83
  5482.3 1923.35  5541.5 1924.17  5591.7 1923.96  5631.9 1924.85  5674.6 1926.99
  5792.8 1929.41  5853.1 1929.77  5873.2 1930.76  5923.5 1931.30  6019.6 1934.02
#Mann=3,-1,0
  4799.9    0.05       0  5009.8    0.05       0  5018.6    0.05       0
Bank Sta=5009.8,5018.6
Exp/Cntr=0.3,0.1