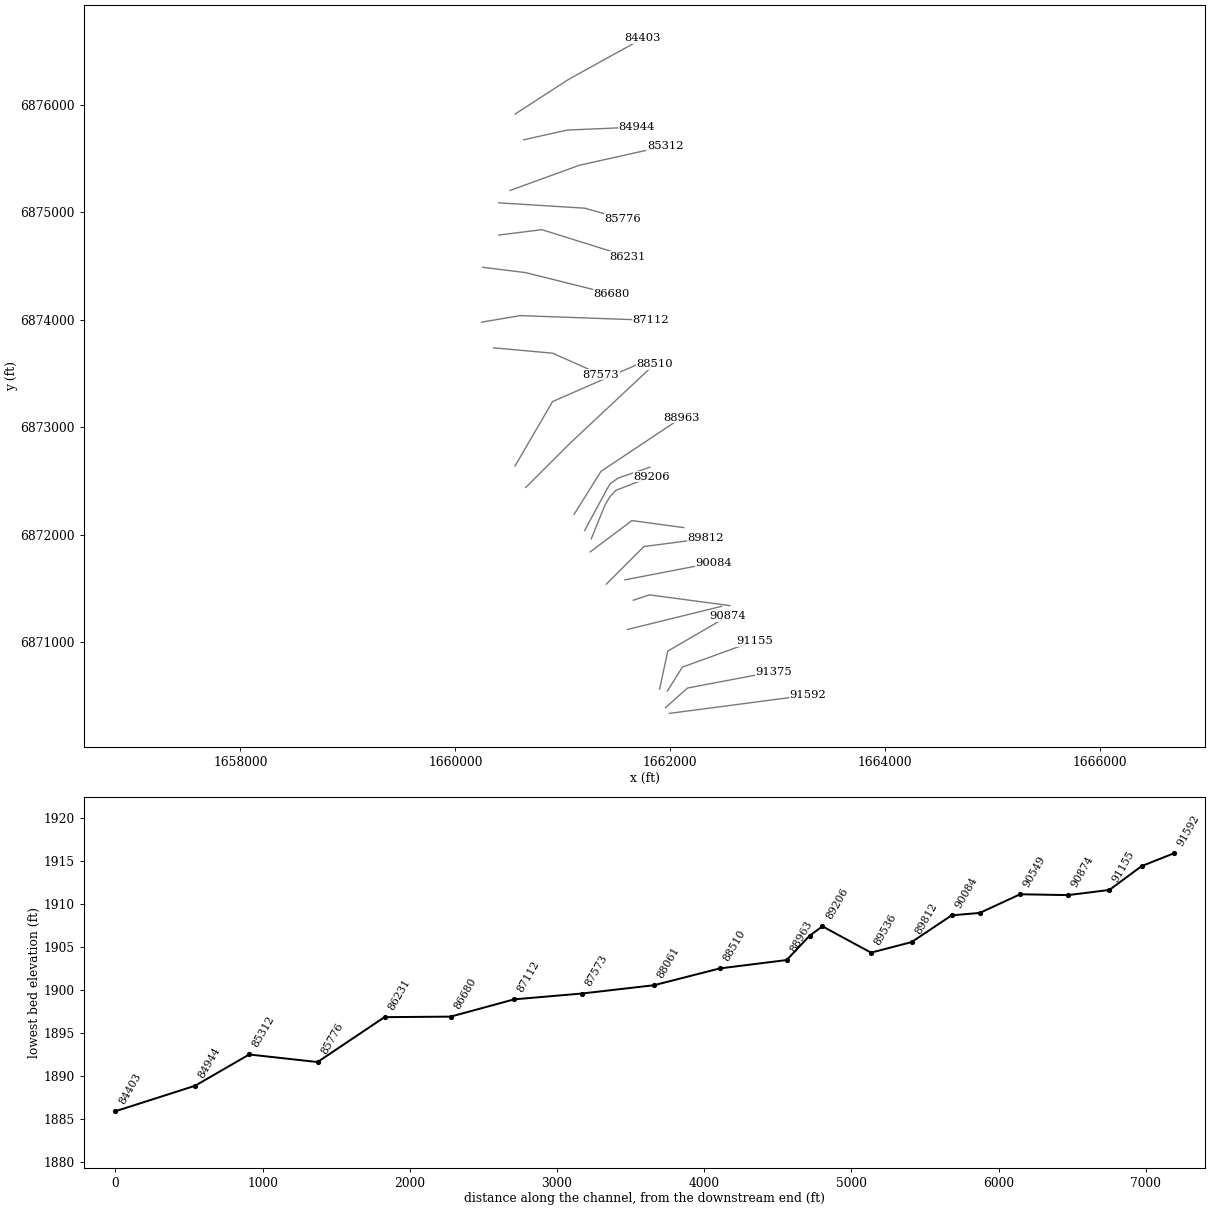
HEC-RAS study Spring Creek.prj: Spring Creek Base Level Engineering

--- Spring Creek.g01 (geometry) --- (continued)

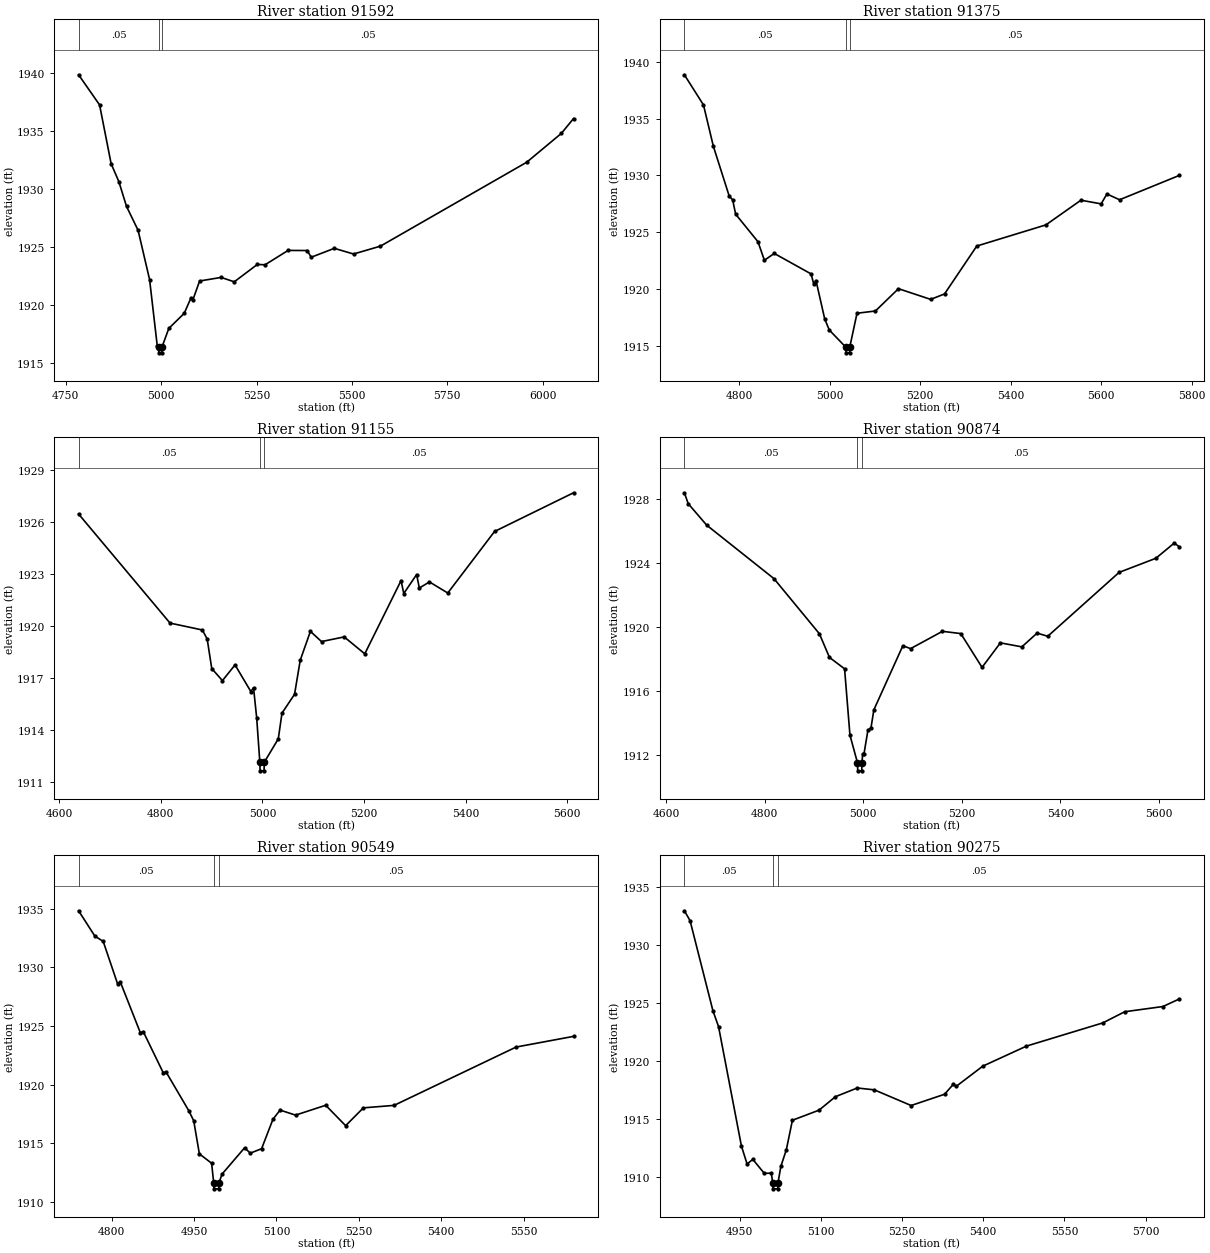
Type RM Length L Ch R = 1,91592,217,217,217
BEGIN DESCRIPTION:
Spring Creek 155.0
END DESCRIPTION:
XS GIS Cut Line= 3
      1661990.40      6870334.70      1662205.69      6870362.48
      1663276.67      6870503.52
#Sta/Elev= 30
  4783.5 1939.87  4838.5 1937.27  4868.8 1932.19  4889.0 1930.65  4909.1 1928.51
  4939.4 1926.45  4969.6 1922.19  4989.8 1916.44  4993.3 1916.37  4993.8 1915.87
  5001.6 1915.87  5002.1 1916.37  5020.0 1917.98  5060.4 1919.28  5078.3 1920.63
  5083.4 1920.47  5100.7 1922.07  5157.0 1922.38  5191.5 1922.00  5252.0 1923.50
  5272.2 1923.47  5332.7 1924.71  5382.8 1924.70  5393.2 1924.12  5453.8 1924.89
  5504.2 1924.40  5574.8 1925.08  5958.1 1932.32  6048.9 1934.81  6080.8 1936.09
#Mann=3,-1,0
  4783.5    0.05       0  4993.3    0.05       0  5002.1    0.05       0
Bank Sta=4993.3,5002.1
Exp/Cntr=0.3,0.1

Type RM Length L Ch R = 1,91375,220,220,220
BEGIN DESCRIPTION:
Spring Creek 154.0
END DESCRIPTION:
XS GIS Cut Line= 3
      1661955.01      6870388.01      1662160.56      6870570.81
      1662964.54      6870723.29
#Sta/Elev= 30
  4679.3 1938.85  4721.5 1936.20  4743.3 1932.57  4778.4 1928.18  4785.9 1927.86
  4792.6 1926.59  4841.9 1924.17  4856.1 1922.54  4877.9 1923.14  4959.2 1921.34
  4965.1 1920.46  4970.1 1920.76  4989.4 1917.37  4999.6 1916.40  5035.9 1914.90
  5036.4 1914.40  5044.2 1914.40  5044.7 1914.90  5060.7 1917.88  5101.4 1918.08
  5152.3 1920.04  5223.5 1919.10  5254.1 1919.58  5325.3 1923.79  5478.0 1925.65
  5555.4 1927.82  5600.1 1927.50  5612.8 1928.37  5640.8 1927.86  5772.7 1930.00
#Mann=3,-1,0
  4679.3    0.05       0  5035.9    0.03       0  5044.7    0.05       0
Bank Sta=5035.9,5044.7
Exp/Cntr=0.3,0.1

Type RM Length L Ch R = 1,91155,281,281,281
BEGIN DESCRIPTION:
Mapping XS e372e210
END DESCRIPTION:
XS GIS Cut Line= 3
      1661973.06      6870543.05      1662111.94      6870765.26
      1662781.05      6871007.94
#Sta/Elev= 30
  4638.3 1926.48  4818.2 1920.17  4881.8 1919.77  4891.3 1919.25  4900.3 1917.54
  4921.3 1916.84  4946.1 1917.75  4977.2 1916.21  4982.5 1916.43  4988.7 1914.69
  4994.9 1912.12  4995.4 1911.62  5003.2 1911.62  5003.7 1912.12  5031.2 1913.47
  5038.5 1914.96  5063.2 1916.05  5074.4 1918.02  5094.4 1919.69  5116.3 1919.10
  5160.9 1919.37  5201.4 1918.39  5272.8 1922.63  5278.1 1921.88  5303.4 1922.98
  5308.7 1922.20  5328.7 1922.55  5364.7 1921.91  5456.7 1925.47  5612.1 1927.71
#Mann=3,-1,0
  4638.3    0.05       0  4994.9    0.03       0  5003.7    0.05       0
Bank Sta=4994.9,5003.7
Exp/Cntr=0.3,0.1

Type RM Length L Ch R = 1,90874,325,325,325
BEGIN DESCRIPTION:
Spring Creek 153.0
END DESCRIPTION:
XS GIS Cut Line= 3
      1661900.13      6870560.36      1661976.53      6870914.56
      1662531.01      6871236.86
#Sta/Elev= 30
  4637.4 1928.38  4645.2 1927.70  4682.6 1926.36  4819.1 1923.02  4911.2 1919.58
  4931.7 1918.10  4962.3 1917.39  4973.2 1913.25  4988.5 1911.52  4989.0 1911.02
  4997.1 1911.02  4997.6 1911.52  4999.0 1912.10  5001.8 1912.10  5009.6 1913.55
  5015.9 1913.71  5021.7 1914.83  5080.5 1918.83  5096.2 1918.65  5160.8 1919.73
  5198.0 1919.59  5241.1 1917.48  5278.3 1919.01  5321.8 1918.76  5352.8 1919.62
  5374.3 1919.42  5519.1 1923.41  5593.6 1924.29  5630.9 1925.24  5641.1 1925.01
#Mann=3,-1,0
  4637.4    0.05       0  4988.5    0.03       0  4997.6    0.05       0
Bank Sta=4988.5,4997.6
Exp/Cntr=0.3,0.1

Type RM Length L Ch R = 1,90549,274,274,274
BEGIN DESCRIPTION:
Mapping XS b4cef50f
END DESCRIPTION:
XS GIS Cut Line= 2
      1661601.48      6871115.94      1662476.49      6871331.22
#Sta/Elev= 30
  4739.7 1934.81  4769.2 1932.66  4784.5 1932.20  4810.7 1928.58  4815.8 1928.73
  4852.2 1924.41  4857.4 1924.52  4893.7 1921.02  4898.9 1921.08  4940.4 1917.77
  4949.3 1916.92  4959.6 1914.10  4981.9 1913.30  4985.7 1911.62  4986.2 1911.12
  4994.8 1911.12  4995.3 1911.62  5000.8 1912.37  5042.0 1914.62  5052.3 1914.16
  5072.9 1914.54  5093.5 1917.04  5106.5 1917.83  5134.7 1917.40  5189.6 1918.24
  5225.9 1916.50  5258.2 1918.02  5314.1 1918.23  5536.3 1923.20  5640.8 1924.11
#Mann=3,-1,0
  4739.7    0.05       0  4985.7    0.03       0  4995.3    0.05       0
Bank Sta=4985.7,4995.3
Exp/Cntr=0.3,0.1

Type RM Length L Ch R = 1,90275,191,191,191
BEGIN DESCRIPTION:
Spring Creek 152.0
END DESCRIPTION:
XS GIS Cut Line= 3
      1661655.02      6871388.01      1661805.00      6871438.00
      1662554.97      6871338.00
#Sta/Elev= 30
  4847.5 1932.91  4858.0 1932.06  4900.2 1924.31  4910.7 1922.92  4952.9 1912.65
  4963.4 1911.09  4974.0 1911.49  4995.1 1910.29  5008.1 1910.30  5010.9 1909.45
  5011.4 1908.95  5020.0 1908.95  5020.5 1909.45  5025.8 1910.88  5035.9 1912.31
  5047.2 1914.86  5096.4 1915.73  5126.7 1916.89  5167.0 1917.64  5198.5 1917.48
  5266.6 1916.13  5328.4 1917.10  5344.8 1917.97  5349.9 1917.78  5399.0 1919.52
  5479.8 1921.25  5621.0 1923.25  5661.3 1924.21  5732.0 1924.66  5762.2 1925.31
#Mann=3,-1,0
  4847.5    0.05       0  5010.9    0.03       0  5020.5    0.05       0
Bank Sta=5010.9,5020.5
Exp/Cntr=0.3,0.1

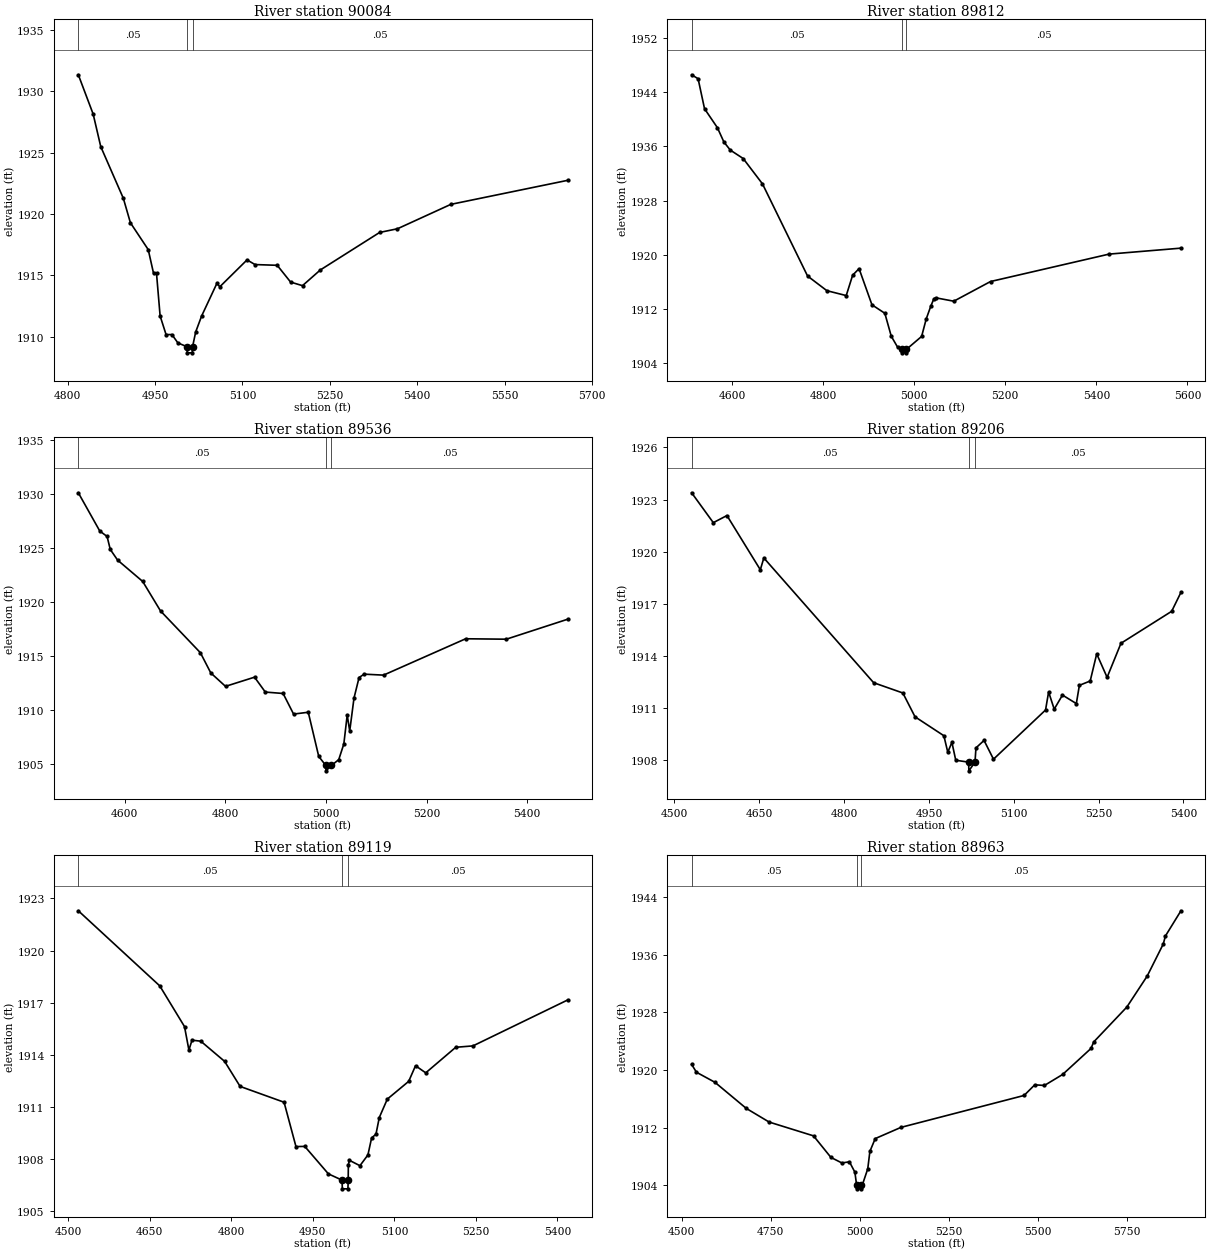
Type RM Length L Ch R = 1,90084,272,272,272
BEGIN DESCRIPTION:
Mapping XS 1960dbd7
END DESCRIPTION:
XS GIS Cut Line= 2
      1661577.18      6871577.75      1662401.82      6871737.13
#Sta/Elev= 30
  4818.2 1931.35  4843.7 1928.14  4856.7 1925.49  4895.5 1921.27  4907.6 1919.28
  4938.2 1917.09  4947.3 1915.16  4952.4 1915.16  4958.6 1911.68  4968.8 1910.16
  4978.9 1910.16  4989.1 1909.48  5004.7 1909.17  5005.2 1908.67  5013.8 1908.67
  5014.3 1909.17  5019.7 1910.38  5029.9 1911.68  5056.0 1914.33  5061.1 1914.06
  5107.8 1916.25  5121.5 1915.87  5159.6 1915.81  5182.6 1914.44  5203.0 1914.15
  5233.6 1915.43  5335.4 1918.49  5366.0 1918.79  5457.6 1920.78  5658.1 1922.74
#Mann=3,-1,0
  4818.2    0.05       0  5004.7    0.03       0  5014.3    0.05       0
Bank Sta=5004.7,5014.3
Exp/Cntr=0.3,0.1

Type RM Length L Ch R = 1,89812,276,276,276
BEGIN DESCRIPTION:
Spring Creek 151.0
END DESCRIPTION:
XS GIS Cut Line= 3
      1661404.97      6871537.97      1661755.00      6871888.00
      1662329.71      6871963.04
#Sta/Elev= 30
  4511.2 1946.54  4525.4 1945.96  4539.5 1941.54  4567.8 1938.74  4582.0 1936.64
  4596.1 1935.44  4624.4 1934.20  4666.8 1930.46  4765.8 1916.88  4808.2 1914.72
  4850.7 1914.00  4864.8 1917.00  4878.9 1917.97  4907.2 1912.64  4935.5 1911.39
  4949.6 1908.01  4963.8 1906.36  4973.1 1906.06  4973.6 1905.56  4982.2 1905.56
  4982.7 1906.06  5016.3 1907.98  5026.4 1910.56  5036.5 1912.45  5043.2 1913.53
  5048.2 1913.66  5086.9 1913.17  5167.6 1916.07  5427.9 1920.11  5585.8 1920.99
#Mann=3,-1,0
  4511.2    0.05       0  4973.1    0.03       0  4982.7    0.05       0
Bank Sta=4973.1,4982.7
Exp/Cntr=0.3,0.1

Type RM Length L Ch R = 1,89536,330,330,330
BEGIN DESCRIPTION:
Spring Creek 150.0
END DESCRIPTION:
XS GIS Cut Line= 3
      1661255.04      6871838.03      1661643.19      6872129.84
      1662125.80      6872063.87
#Sta/Elev= 30
  4507.6 1930.10  4550.2 1926.56  4564.8 1926.05  4571.1 1924.85  4585.7 1923.86
  4635.6 1921.88  4671.0 1919.15  4750.2 1915.28  4771.0 1913.40  4800.2 1912.16
  4857.9 1913.01  4879.3 1911.63  4914.7 1911.50  4935.5 1909.59  4964.7 1909.76
  4985.5 1905.67  4999.5 1904.83  5000.0 1904.33  5010.8 1904.83  5025.3 1905.37
  5035.4 1906.82  5042.1 1909.50  5047.1 1908.02  5055.6 1911.07  5065.7 1912.98
  5075.8 1913.29  5114.3 1913.20  5277.6 1916.57  5358.4 1916.53  5480.3 1918.38
#Mann=3,-1,0
  4507.6    0.05       0  4999.5    0.03       0  5010.8    0.05       0
Bank Sta=4999.5,5010.8
Exp/Cntr=0.3,0.1

Type RM Length L Ch R = 1,89206,87,87,87
BEGIN DESCRIPTION:
Mapping XS d83c31bc
END DESCRIPTION:
XS GIS Cut Line= 5
      1661264.74      6871959.74      1661389.72      6872268.73
      1661438.33      6872352.06      1661493.89      6872411.09
      1661823.71      6872539.55
#Sta/Elev= 30
  4530.7 1923.39  4569.0 1921.67  4593.1 1922.08  4652.1 1918.96  4658.3 1919.64
  4852.4 1912.46  4904.0 1911.87  4925.5 1910.50  4976.5 1909.41  4983.4 1908.46
  4990.7 1909.03  4997.5 1908.00  5020.2 1907.89  5020.7 1907.39  5031.5 1907.89
  5033.2 1908.71  5047.5 1909.14  5064.2 1908.06  5156.2 1910.89  5161.6 1911.93
  5171.5 1910.94  5186.1 1911.75  5210.6 1911.26  5216.0 1912.31  5235.1 1912.56
  5246.6 1914.12  5265.0 1912.77  5289.5 1914.73  5379.1 1916.57  5395.5 1917.66
#Mann=3,-1,0
  4530.7    0.05       0  5020.2    0.03       0  5031.5    0.05       0
Bank Sta=5020.2,5031.5
Exp/Cntr=0.3,0.1

Type RM Length L Ch R = 1,89119,156,156,156
BEGIN DESCRIPTION:
Mapping XS 35fb89d7
END DESCRIPTION:
XS GIS Cut Line= 5
      1661202.20      6872036.05      1661414.03      6872428.45
      1661441.81      6872473.59      1661514.72      6872525.67
      1661809.88      6872626.38
#Sta/Elev= 30
  4518.4 1922.29  4668.3 1917.97  4713.8 1915.63  4721.9 1914.28  4727.6 1914.85
  4743.8 1914.79  4787.6 1913.63  4816.1 1912.19  4897.0 1911.28  4918.9 1908.73
  4935.1 1908.74  4978.6 1907.16  5003.7 1906.80  5004.2 1906.30  5014.5 1906.30
  5015.0 1906.80  5015.3 1907.69  5017.3 1907.94  5036.6 1907.63  5051.3 1908.25
  5058.1 1909.23  5066.1 1909.44  5072.2 1910.40  5087.0 1911.46  5126.3 1912.48
  5138.9 1913.38  5157.7 1912.97  5212.9 1914.44  5244.6 1914.52  5418.8 1917.16
#Mann=3,-1,0
  4518.4    0.05       0  5003.7    0.03       0  5015.0    0.05       0
Bank Sta=5003.7,5015
Exp/Cntr=0.3,0.1

Type RM Length L Ch R = 1,88963,453,453,453
BEGIN DESCRIPTION:
Spring Creek 149.0
END DESCRIPTION:
XS GIS Cut Line= 3
      1661105.01      6872188.02      1661355.00      6872588.00
      1662105.03      6873088.02
#Sta/Elev= 30
  4528.2 1920.78  4541.7 1919.69  4593.6 1918.29  4681.5 1914.66  4745.7 1912.76
  4870.2 1910.84  4919.1 1907.84  4949.8 1907.07  4971.0 1907.23  4986.3 1905.79
  4991.2 1903.97  4991.7 1903.47  5002.1 1903.47  5002.6 1903.97  5007.4 1904.04
  5022.4 1906.25  5028.4 1908.68  5043.4 1910.46  5115.6 1912.02  5461.1 1916.46
  5491.1 1917.94  5518.2 1917.85  5569.3 1919.38  5648.9 1923.00  5656.4 1923.90
  5749.5 1928.76  5806.6 1933.07  5851.7 1937.53  5857.7 1938.64  5901.3 1942.15
#Mann=3,-1,0
  4528.2    0.05       0  4991.2    0.03       0  5002.6    0.05       0
Bank Sta=4991.2,5002.6
Exp/Cntr=0.3,0.1

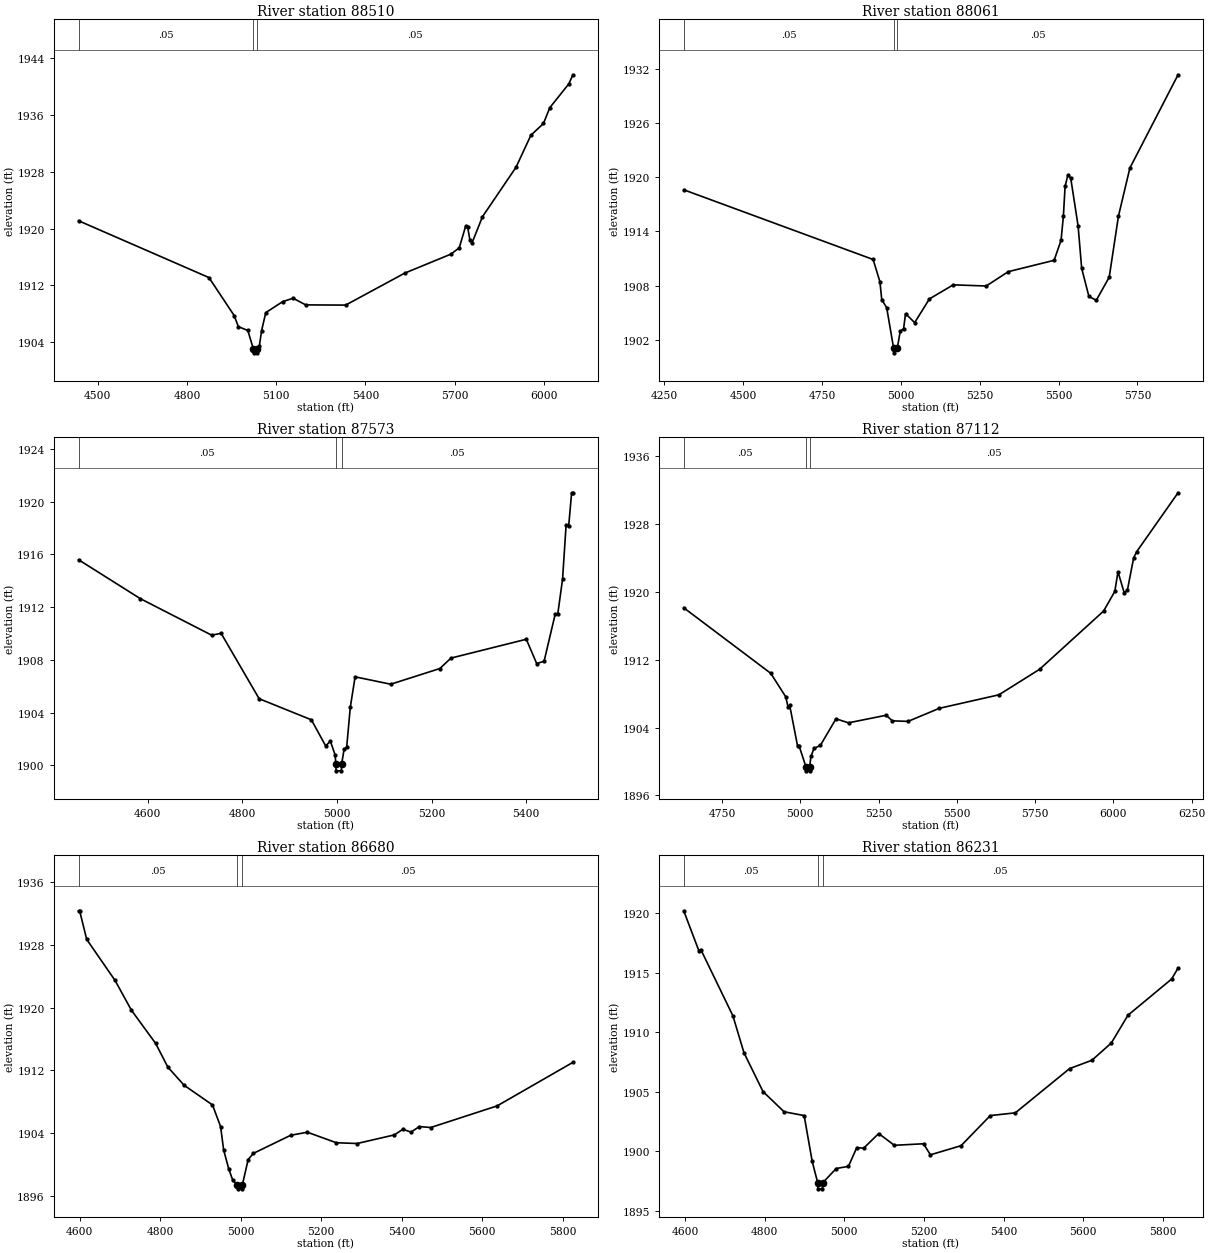
Type RM Length L Ch R = 1,88510,449,449,449
BEGIN DESCRIPTION:
Spring Creek 148.0
END DESCRIPTION:
XS GIS Cut Line= 3
      1660654.97      6872437.97      1661055.00      6872838.00
      1661854.99      6873587.99
#Sta/Elev= 30
  4435.2 1921.12  4873.7 1913.11  4958.5 1907.75  4972.6 1906.19  5004.4 1905.65
  5023.3 1903.00  5023.8 1902.50  5034.2 1902.50  5034.7 1903.00  5043.2 1903.47
  5050.5 1905.60  5064.7 1908.17  5121.3 1909.71  5156.5 1910.20  5199.0 1909.26
  5333.3 1909.23  5531.6 1913.73  5687.0 1916.41  5715.3 1917.30  5736.8 1920.36
  5743.6 1920.22  5751.0 1918.44  5757.8 1917.95  5793.4 1921.69  5906.3 1928.67
  5956.1 1933.17  5998.6 1934.84  6019.6 1937.05  6083.6 1940.41  6097.5 1941.70
#Mann=3,-1,0
  4435.2    0.05       0  5023.3    0.03       0  5034.7    0.05       0
Bank Sta=5023.3,5034.7
Exp/Cntr=0.3,0.1

Type RM Length L Ch R = 1,88061,488,488,488
BEGIN DESCRIPTION:
Spring Creek 147.0
END DESCRIPTION:
XS GIS Cut Line= 3
      1660554.98      6872637.97      1660905.00      6873238.00
      1661705.03      6873588.01
#Sta/Elev= 30
  4311.0 1918.62  4911.8 1910.89  4933.3 1908.42  4939.1 1906.44  4954.8 1905.54
  4976.8 1901.04  4977.3 1900.54  4988.2 1901.04  4997.8 1902.92  5008.4 1903.23
  5014.6 1904.88  5043.5 1903.89  5090.3 1906.52  5165.9 1908.08  5270.4 1907.95
  5340.5 1909.54  5485.9 1910.80  5507.8 1913.02  5515.2 1915.68  5520.6 1918.99
  5529.6 1920.28  5538.6 1919.89  5561.9 1914.60  5573.2 1909.91  5596.2 1906.79
  5619.6 1906.37  5660.6 1908.93  5689.8 1915.69  5726.1 1921.03  5878.9 1931.37
#Mann=3,-1,0
  4311.0    0.05       0  4976.8    0.05       0  4988.2    0.05       0
Bank Sta=4976.8,4988.2
Exp/Cntr=0.3,0.1

Type RM Length L Ch R = 1,87573,461,461,461
BEGIN DESCRIPTION:
Spring Creek 146.0
END DESCRIPTION:
XS GIS Cut Line= 3
      1660354.99      6873738.00      1660905.00      6873688.00
      1661354.98      6873488.01
#Sta/Elev= 30
  4453.9 1915.59  4584.4 1912.64  4735.1 1909.87  4755.1 1910.01  4835.5 1905.05
  4945.9 1903.45  4976.1 1901.47  4986.1 1901.83  4996.1 1900.78  4997.6 1900.08
  4998.1 1899.58  5009.3 1899.58  5009.8 1900.08  5015.1 1901.23  5020.5 1901.37
  5028.1 1904.39  5038.3 1906.71  5113.6 1906.15  5217.5 1907.34  5240.8 1908.13
  5400.1 1909.56  5422.0 1907.72  5437.7 1907.89  5461.0 1911.44  5466.5 1911.45
  5476.7 1914.11  5484.3 1918.26  5489.7 1918.17  5495.9 1920.67  5498.6 1920.67
#Mann=3,-1,0
  4453.9    0.05       0  4997.6    0.03       0  5009.8    0.05       0
Bank Sta=4997.6,5009.8
Exp/Cntr=0.3,0.1

Type RM Length L Ch R = 1,87112,432,432,432
BEGIN DESCRIPTION:
Spring Creek 145.0
END DESCRIPTION:
XS GIS Cut Line= 3
      1660243.86      6873977.06      1660605.00      6874038.00
      1661816.77      6873994.42
#Sta/Elev= 30
  4627.6 1918.12  4905.7 1910.39  4953.3 1907.63  4961.1 1906.39  4966.1 1906.61
  4991.3 1901.81  4996.3 1901.81  5017.8 1899.40  5018.3 1898.90  5029.5 1898.90
  5030.0 1899.40  5033.9 1900.61  5043.9 1901.55  5063.9 1901.89  5113.9 1905.03
  5153.9 1904.56  5274.0 1905.45  5294.0 1904.79  5344.1 1904.73  5444.1 1906.27
  5634.3 1907.86  5764.3 1910.87  5968.6 1917.73  6004.5 1920.05  6014.5 1922.36
  6034.5 1919.88  6044.5 1920.17  6064.5 1923.99  6074.5 1924.74  6206.4 1931.67
#Mann=3,-1,0
  4627.6    0.05       0  5017.8    0.03       0  5030.0    0.05       0
Bank Sta=5017.8,5030
Exp/Cntr=0.3,0.1

Type RM Length L Ch R = 1,86680,449,449,449
BEGIN DESCRIPTION:
Spring Creek 144.0
END DESCRIPTION:
XS GIS Cut Line= 3
      1660254.96      6874488.01      1660655.00      6874438.00
      1661455.02      6874237.99
#Sta/Elev= 30
  4597.6 1932.35  4600.2 1932.35  4617.8 1928.70  4688.3 1923.46  4728.7 1919.68
  4789.1 1915.43  4819.4 1912.41  4859.7 1910.10  4930.2 1907.59  4950.4 1904.82
  4957.9 1901.85  4970.5 1899.45  4980.6 1897.98  4992.1 1897.39  4992.6 1896.89
  5003.9 1896.89  5004.4 1897.39  5018.8 1900.63  5031.7 1901.41  5124.4 1903.72
  5165.7 1904.11  5237.8 1902.77  5289.4 1902.67  5382.1 1903.77  5402.8 1904.48
  5423.4 1904.13  5444.0 1904.83  5472.3 1904.71  5637.3 1907.47  5825.4 1913.02
#Mann=3,-1,0
  4597.6    0.05       0  4992.1    0.03       0  5004.4    0.05       0
Bank Sta=4992.1,5004.4
Exp/Cntr=0.3,0.1

Type RM Length L Ch R = 1,86231,455,455,455
BEGIN DESCRIPTION:
Spring Creek 143.0
END DESCRIPTION:
XS GIS Cut Line= 3
      1660404.96      6874787.99      1660805.00      6874838.00
      1661604.99      6874588.00
#Sta/Elev= 30
  4597.0 1920.21  4634.8 1916.87  4639.9 1916.95  4720.5 1911.38  4748.2 1908.28
  4796.1 1905.01  4849.0 1903.31  4899.4 1902.99  4919.5 1899.16  4933.5 1897.33
  4934.0 1896.83  4945.3 1896.83  4945.8 1897.33  4980.0 1898.54  5010.6 1898.72
  5031.6 1900.30  5048.9 1900.25  5086.6 1901.48  5125.9 1900.49  5199.2 1900.62
  5216.5 1899.69  5293.5 1900.46  5366.8 1902.99  5429.7 1903.22  5565.9 1906.94
  5622.0 1907.64  5670.7 1909.09  5712.6 1911.43  5822.1 1914.47  5838.3 1915.39
#Mann=3,-1,0
  4597.0    0.05       0  4933.5    0.05       0  4945.8    0.05       0
Bank Sta=4933.5,4945.8
Exp/Cntr=0.3,0.1

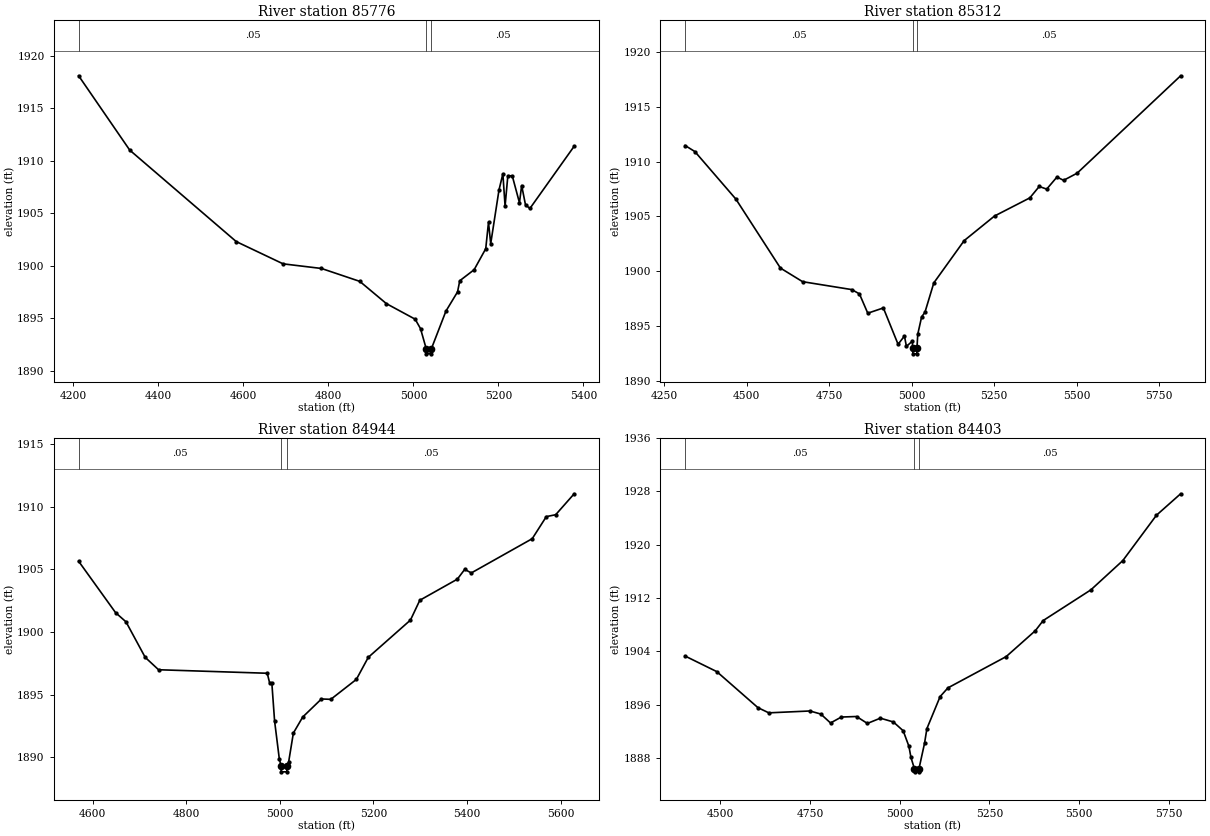
Type RM Length L Ch R = 1,85776,464,464,464
BEGIN DESCRIPTION:
Spring Creek 142.0
END DESCRIPTION:
XS GIS Cut Line= 3
      1660405.03      6875088.00      1661205.00      6875038.00
      1661554.97      6874938.01
#Sta/Elev= 30
  4212.6 1918.09  4332.8 1911.01  4583.3 1902.30  4693.5 1900.18  4783.7 1899.74
  4873.9 1898.51  4936.5 1896.39  5004.1 1894.91  5016.7 1894.01  5030.0 1892.11
  5030.5 1891.61  5041.9 1891.61  5042.4 1892.11  5076.5 1895.68  5103.8 1897.51
  5109.0 1898.57  5142.8 1899.62  5170.1 1901.62  5176.6 1904.14  5181.8 1902.10
  5201.3 1907.22  5210.4 1908.75  5215.6 1905.68  5222.1 1908.57  5232.5 1908.56
  5249.4 1906.00  5254.6 1907.64  5263.7 1905.78  5274.1 1905.46  5378.1 1911.38
#Mann=3,-1,0
  4212.6    0.05       0  5030.0    0.03       0  5042.4    0.05       0
Bank Sta=5030,5042.4
Exp/Cntr=0.3,0.1

Type RM Length L Ch R = 1,85312,368,368,368
BEGIN DESCRIPTION:
Spring Creek 141.0
END DESCRIPTION:
XS GIS Cut Line= 3
      1660510.34      6875203.58      1661155.00      6875438.00
      1661951.15      6875615.71
#Sta/Elev= 30
  4313.7 1911.46  4343.3 1910.91  4467.6 1906.58  4602.6 1900.30  4669.8 1899.06
  4818.8 1898.34  4842.0 1897.95  4867.3 1896.19  4914.5 1896.67  4959.1 1893.36
  4978.4 1894.11  4984.4 1893.17  5002.2 1893.64  5003.5 1892.99  5004.0 1892.49
  5015.8 1892.49  5016.3 1892.99  5018.8 1894.28  5030.4 1895.85  5040.6 1896.28
  5067.4 1898.95  5159.4 1902.80  5251.4 1905.04  5358.3 1906.69  5386.9 1907.73
  5409.5 1907.49  5440.6 1908.59  5460.7 1908.29  5501.7 1908.94  5815.4 1917.81
#Mann=3,-1,0
  4313.7    0.05       0  5003.5    0.03       0  5016.3    0.05       0
Bank Sta=5003.5,5016.3
Exp/Cntr=0.3,0.1

Type RM Length L Ch R = 1,84944,541,541,541
BEGIN DESCRIPTION:
Spring Creek 140.0
END DESCRIPTION:
XS GIS Cut Line= 3
      1660636.27      6875674.98      1661039.03      6875765.26
      1661684.48      6875793.02
#Sta/Elev= 30
  4570.1 1905.64  4649.1 1901.54  4671.3 1900.81  4712.3 1897.98  4740.9 1896.99
  4973.1 1896.71  4978.2 1895.94  4982.9 1895.94  4988.8 1892.90  4998.8 1889.91
  5002.4 1889.35  5002.9 1888.85  5014.8 1888.85  5015.3 1889.35  5018.9 1889.65
  5028.9 1891.94  5048.9 1893.22  5088.9 1894.66  5108.9 1894.63  5163.5 1896.22
  5189.0 1897.98  5279.1 1900.95  5299.1 1902.53  5379.2 1904.21  5395.0 1904.99
  5409.2 1904.71  5539.3 1907.44  5569.4 1909.20  5589.4 1909.35  5628.9 1911.02
#Mann=3,-1,0
  4570.1    0.05       0  5002.4    0.03       0  5015.3    0.05       0
Bank Sta=5002.4,5015.3
Exp/Cntr=0.3,0.1

Type RM Length L Ch R = 1,84403,415,415,415
BEGIN DESCRIPTION:
Spring Creek 139.0
END DESCRIPTION:
XS GIS Cut Line= 3
      1660556.40      6875914.57      1661055.00      6876238.00
      1661743.93      6876619.45
#Sta/Elev= 30
  4401.7 1903.28  4490.1 1900.94  4604.8 1895.53  4635.1 1894.75  4749.8 1895.03
  4780.1 1894.57  4807.2 1893.23  4837.5 1894.12  4879.7 1894.20  4910.0 1893.16
  4946.2 1893.95  4982.5 1893.38  5009.8 1892.06  5025.8 1889.73  5031.5 1888.05
  5041.0 1886.39  5041.5 1885.89  5053.5 1885.89  5054.0 1886.39  5069.3 1890.16
  5076.0 1892.39  5112.8 1897.19  5134.6 1898.50  5297.1 1903.20  5378.4 1907.09
  5400.2 1908.61  5533.2 1913.22  5622.3 1917.62  5716.1 1924.43  5783.5 1927.65
#Mann=3,-1,0
  4401.7    0.05       0  5041.0    0.03       0  5054.0    0.05       0
Bank Sta=5041,5054
Exp/Cntr=0.3,0.1