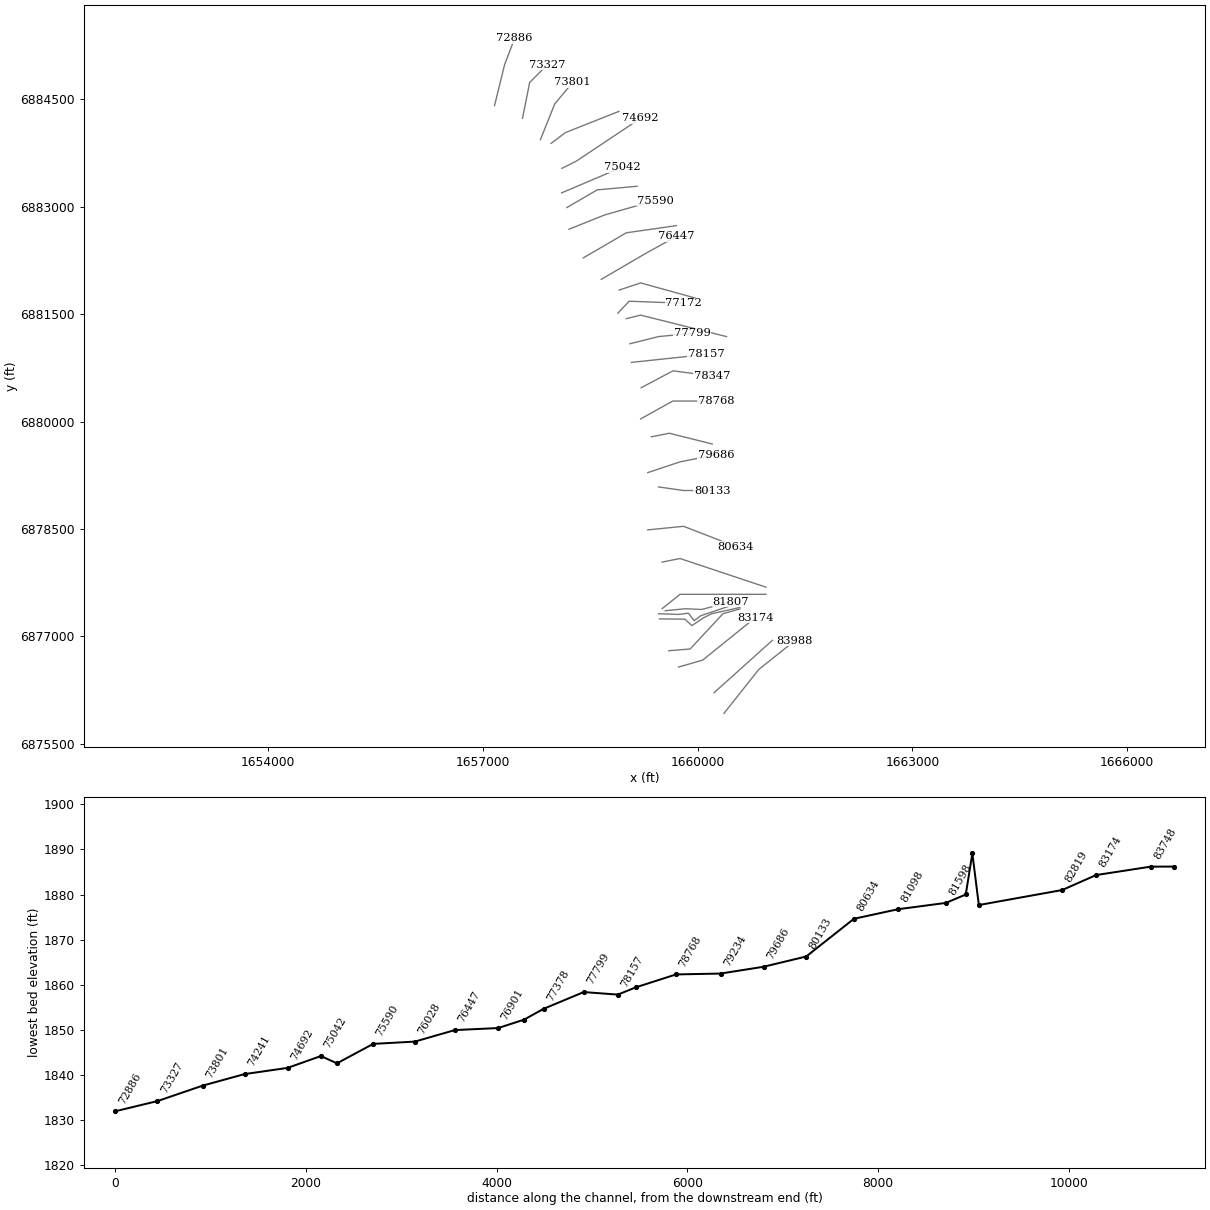
HEC-RAS study Spring Creek.prj: Spring Creek Base Level Engineering

--- Spring Creek.g01 (geometry) --- (continued)

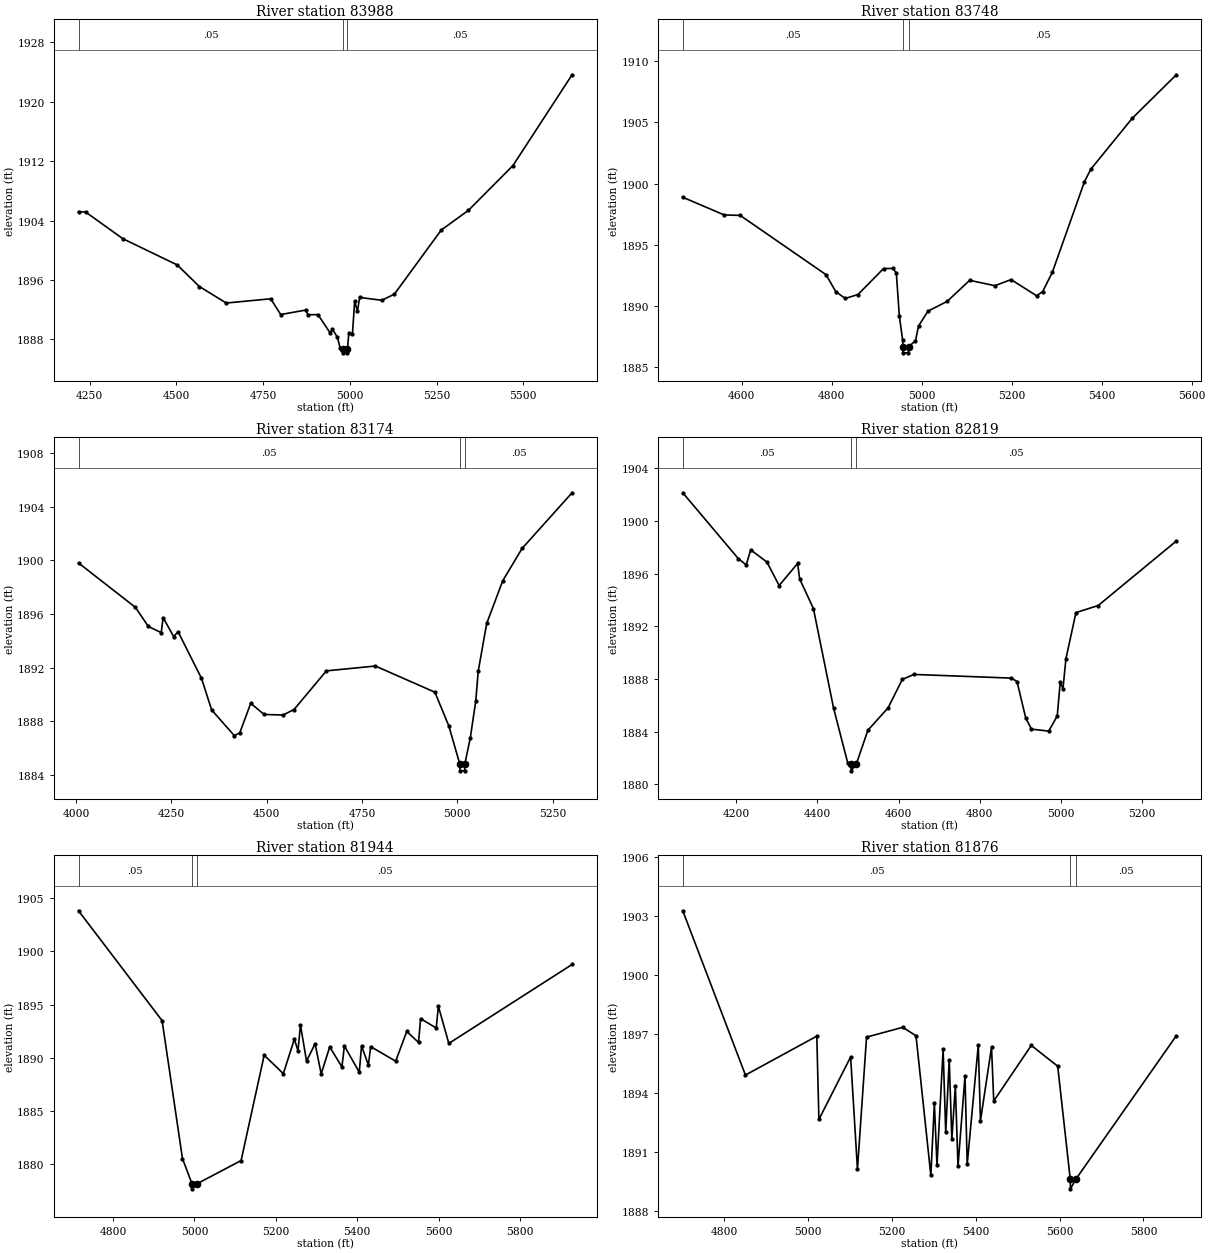
Type RM Length L Ch R = 1,83988,240,240,240
BEGIN DESCRIPTION:
Spring Creek 138.0
END DESCRIPTION:
XS GIS Cut Line= 3
      1660368.90      6875924.99      1660855.00      6876538.00
      1661355.03      6876938.02
#Sta/Elev= 30
  4217.7 1905.19  4238.1 1905.14  4345.5 1901.55  4502.3 1898.02  4566.1 1895.12
  4643.5 1892.90  4771.7 1893.47  4800.5 1891.35  4872.4 1891.95  4879.1 1891.33
  4907.9 1891.34  4943.2 1888.87  4949.5 1889.41  4964.0 1888.29  4972.0 1886.84
  4980.0 1886.70  4980.5 1886.20  4992.5 1886.20  4993.0 1886.70  4996.9 1888.92
  5007.3 1888.71  5013.7 1893.15  5021.7 1891.80  5028.1 1893.65  5092.1 1893.27
  5128.1 1894.09  5263.4 1902.72  5341.8 1905.37  5469.9 1911.38  5640.4 1923.60
#Mann=3,-1,0
  4217.7    0.05       0  4980.0    0.03       0  4993.0    0.05       0
Bank Sta=4980,4993
Exp/Cntr=0.3,0.1

Type RM Length L Ch R = 1,83748,574,574,574
BEGIN DESCRIPTION:
Mapping XS f017b19b
END DESCRIPTION:
XS GIS Cut Line= 2
      1660230.04      6876213.21      1661045.99      6876945.83
#Sta/Elev= 30
  4469.3 1898.89  4561.1 1897.45  4596.9 1897.41  4787.6 1892.57  4809.2 1891.19
  4830.2 1890.63  4858.6 1890.95  4915.4 1893.07  4936.3 1893.08  4943.8 1892.71
  4950.5 1889.19  4958.0 1887.20  4958.2 1886.69  4958.7 1886.19  4970.7 1886.19
  4971.2 1886.69  4986.4 1887.18  4993.1 1888.38  5014.1 1889.59  5056.7 1890.39
  5106.8 1892.11  5162.8 1891.67  5198.7 1892.17  5255.5 1890.85  5269.0 1891.19
  5290.6 1892.78  5361.7 1900.15  5375.9 1901.18  5467.8 1905.33  5565.9 1908.89
#Mann=3,-1,0
  4469.3    0.05       0  4958.2    0.03       0  4971.2    0.05       0
Bank Sta=4958.2,4971.2
Exp/Cntr=0.3,0.1

Type RM Length L Ch R = 1,83174,355,355,355
BEGIN DESCRIPTION:
Mapping XS f9f9417b
END DESCRIPTION:
XS GIS Cut Line= 3
      1659735.02      6876572.30      1660071.24      6876668.62
      1660806.42      6877261.81
#Sta/Elev= 30
  4006.4 1899.81  4155.7 1896.50  4189.5 1895.08  4223.2 1894.62  4228.4 1895.73
  4256.0 1894.32  4267.4 1894.69  4328.8 1891.22  4355.5 1888.86  4414.8 1886.95
  4429.2 1887.14  4458.0 1889.35  4493.2 1888.52  4542.8 1888.48  4571.6 1888.89
  4656.5 1891.77  4785.0 1892.13  4941.0 1890.18  4977.7 1887.66  5006.4 1884.82
  5006.9 1884.32  5019.0 1884.32  5019.5 1884.82  5033.8 1886.76  5048.2 1889.51
  5054.8 1891.76  5076.9 1895.30  5119.1 1898.49  5169.7 1900.89  5300.8 1905.04
#Mann=3,-1,0
  4006.4    0.05       0  5006.4    0.05       0  5019.5    0.05       0
Bank Sta=5006.4,5019.5
Exp/Cntr=0.3,0.1

Type RM Length L Ch R = 1,82819,875,875,875
BEGIN DESCRIPTION:
Mapping XS b4cd40bb
END DESCRIPTION:
XS GIS Cut Line= 4
      1659598.07      6876799.98      1659896.67      6876824.28
      1660355.00      6877317.34      1660590.51      6877383.15
#Sta/Elev= 30
  4067.8 1902.15  4205.2 1897.13  4224.3 1896.67  4235.3 1897.81  4275.4 1896.88
  4305.5 1895.10  4351.1 1896.78  4356.1 1895.60  4390.0 1893.35  4439.8 1885.77
  4475.0 1881.57  4482.6 1881.51  4483.1 1881.01  4495.7 1881.51  4524.3 1884.09
  4574.2 1885.80  4609.3 1887.96  4637.7 1888.34  4878.1 1888.06  4892.2 1887.80
  4913.7 1885.03  4927.9 1884.18  4970.4 1884.03  4991.4 1885.18  4998.8 1887.74
  5005.6 1887.26  5012.9 1889.54  5037.6 1893.04  5092.5 1893.58  5285.1 1898.48
#Mann=3,-1,0
  4067.8    0.05       0  4482.6    0.03       0  4495.7    0.05       0
Bank Sta=4482.6,4495.7
Exp/Cntr=0.3,0.1

Type RM Length L Ch R = 1,81944,68,68,68
BEGIN DESCRIPTION:
Mapping XS 09e11bc2
END DESCRIPTION:
XS GIS Cut Line= 6
      1659469.57      6877244.42      1659823.75      6877240.95
      1659920.97      6877150.67      1660080.69      6877258.31
      1660198.75      6877317.34      1660590.60      6877404.03
#Sta/Elev= 30
  4715.2 1903.82  4920.6 1893.49  4970.6 1880.53  4993.8 1878.18  4994.3 1877.68
  5007.5 1878.18  5114.7 1880.34  5171.4 1890.24  5218.5 1888.51  5245.6 1891.76
  5254.5 1890.66  5260.6 1893.08  5275.5 1889.69  5296.5 1891.32  5311.5 1888.49
  5332.5 1891.02  5362.5 1889.14  5368.5 1891.11  5405.1 1888.65  5410.7 1891.12
  5427.5 1889.32  5433.1 1891.05  5494.6 1889.68  5521.8 1892.48  5550.7 1891.44
  5555.8 1893.68  5594.3 1892.80  5599.4 1894.85  5625.2 1891.35  5928.0 1898.77
#Mann=3,-1,0
  4715.2    0.05       0  4993.8    0.05       0  5007.5    0.05       0
Bank Sta=4993.8,5007.5
Exp/Cntr=0.3,0.1

Type RM Length L Ch R = 1,81876,69,69,69
BEGIN DESCRIPTION:
Mapping XS decdf798
END DESCRIPTION:
XS GIS Cut Line= 6
      1659455.66      6877317.34      1659730.00      6877306.92
      1659872.36      6877324.28      1659952.22      6877220.12
      1660045.97      6877289.56      1660531.08      6877452.42
#Sta/Elev= 30
  4700.9 1903.27  4850.4 1894.91  5020.7 1896.89  5025.7 1892.65  5101.4 1895.83
  5117.7 1890.12  5139.4 1896.84  5225.7 1897.34  5257.4 1896.91  5292.8 1889.81
  5301.2 1893.47  5307.5 1890.32  5322.1 1896.22  5328.3 1891.99  5336.7 1895.69
  5342.9 1891.64  5351.3 1894.35  5357.6 1890.27  5374.3 1894.85  5379.6 1890.37
  5406.0 1896.43  5411.2 1892.58  5437.6 1896.33  5442.9 1893.59  5532.5 1896.42
  5595.5 1895.36  5625.4 1889.62  5625.9 1889.12  5639.1 1889.62  5878.5 1896.91
#Mann=3,-1,0
  4700.9    0.05       0  5625.4    0.03       0  5639.1    0.05       0
Bank Sta=5625.4,5639.1
Exp/Cntr=0.3,0.1

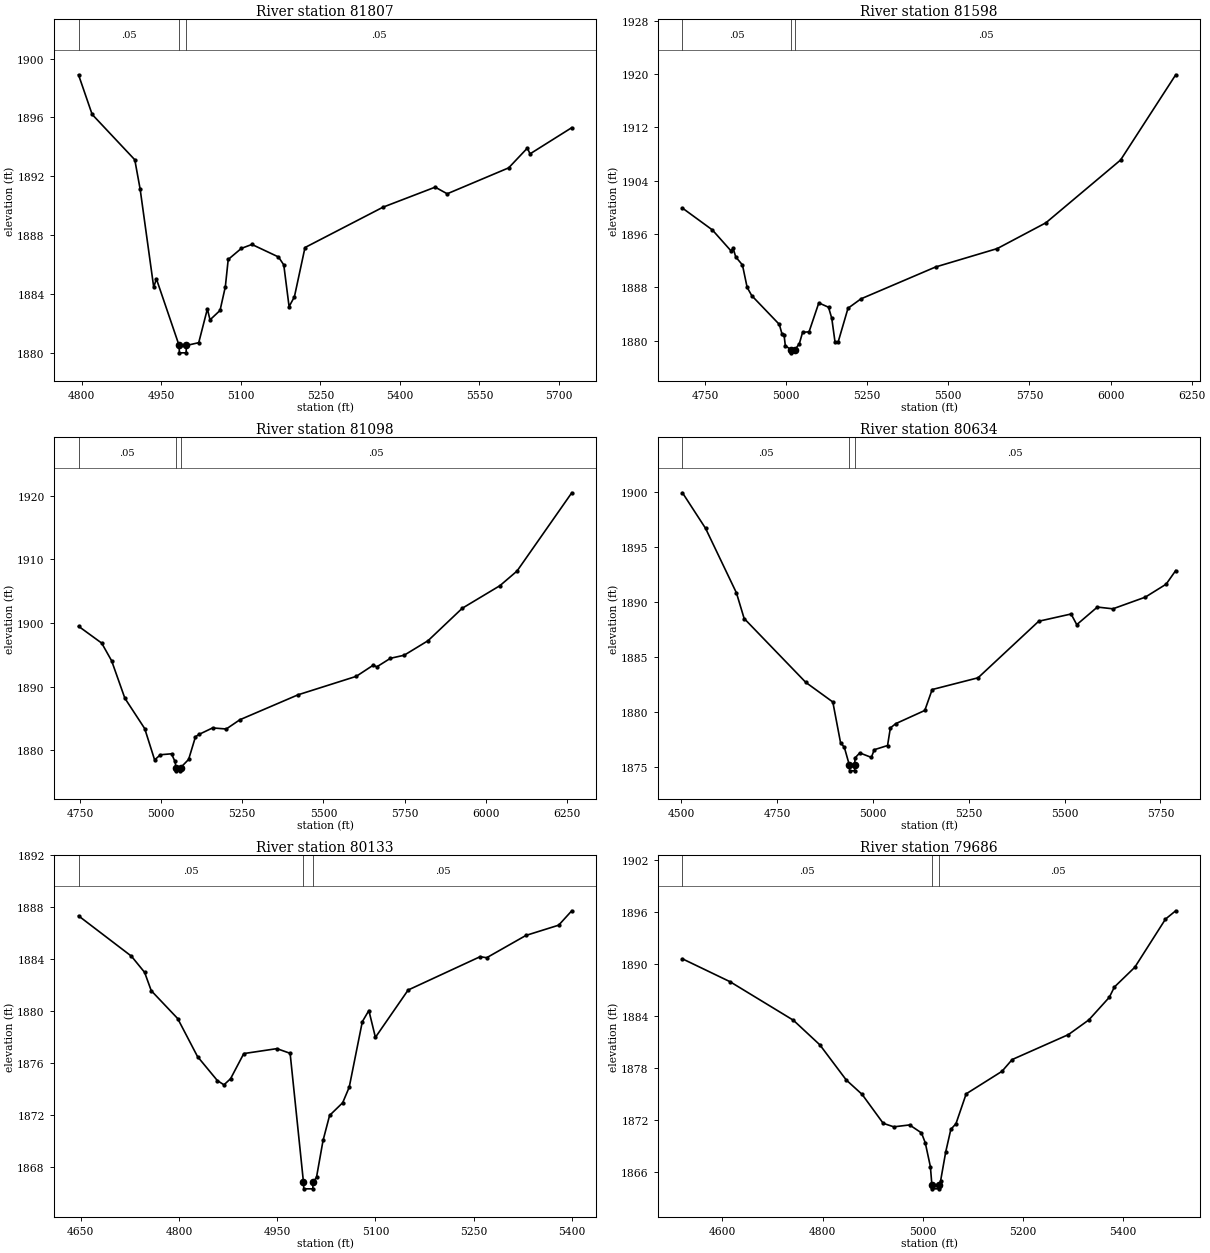
Type RM Length L Ch R = 1,81807,209,209,209
BEGIN DESCRIPTION:
Mapping XS 355eb765
END DESCRIPTION:
XS GIS Cut Line= 4
      1659549.40      6877359.00      1659830.69      6877386.78
      1660056.39      6877376.37      1660464.15      6877483.49
#Sta/Elev= 30
  4794.0 1898.90  4819.7 1896.21  4900.1 1893.13  4910.2 1891.14  4935.8 1884.48
  4940.9 1885.04  4983.7 1880.52  4984.2 1880.02  4996.9 1880.02  4997.4 1880.52
  5020.7 1880.71  5037.0 1883.00  5042.0 1882.26  5060.9 1882.90  5070.9 1884.51
  5076.3 1886.36  5101.0 1887.11  5121.0 1887.38  5171.1 1886.53  5181.1 1885.99
  5191.1 1883.16  5201.1 1883.82  5221.1 1887.17  5368.2 1889.91  5466.6 1891.27
  5489.3 1890.82  5605.2 1892.58  5640.4 1893.92  5645.5 1893.53  5724.2 1895.31
#Mann=3,-1,0
  4794.0    0.05       0  4983.7    0.03       0  4997.4    0.05       0
Bank Sta=4983.7,4997.4
Exp/Cntr=0.3,0.1

Type RM Length L Ch R = 1,81598,500,500,500
BEGIN DESCRIPTION:
Spring Creek 136.0
END DESCRIPTION:
XS GIS Cut Line= 3
      1659504.99      6877387.99      1659755.00      6877588.00
      1660955.03      6877588.00
#Sta/Elev= 30
  4680.5 1899.86  4772.6 1896.59  4830.2 1893.44  4836.6 1893.86  4844.6 1892.54
  4865.4 1891.33  4879.8 1887.97  4894.2 1886.72  4979.1 1882.41  4987.1 1881.00
  4993.5 1880.87  4997.5 1879.23  5013.8 1878.65  5014.3 1878.15  5027.5 1878.65
  5040.7 1879.52  5050.7 1881.22  5070.7 1881.31  5100.7 1885.64  5130.7 1884.99
  5140.7 1883.32  5150.7 1879.77  5160.7 1879.84  5190.7 1884.84  5230.7 1886.25
  5460.7 1891.03  5650.7 1893.79  5800.7 1897.66  6030.7 1907.07  6200.7 1919.86
#Mann=3,-1,0
  4680.5    0.05       0  5013.8    0.03       0  5027.5    0.05       0
Bank Sta=5013.8,5027.5
Exp/Cntr=0.3,0.1

Type RM Length L Ch R = 1,81098,464,464,464
BEGIN DESCRIPTION:
Spring Creek 135.0
END DESCRIPTION:
XS GIS Cut Line= 3
      1659505.01      6878038.00      1659755.00      6878088.00
      1660955.04      6877687.99
#Sta/Elev= 30
  4745.4 1899.50  4816.8 1896.85  4847.4 1894.07  4888.2 1888.18  4949.4 1883.40
  4979.9 1878.48  4997.8 1879.29  5032.0 1879.44  5042.5 1878.24  5046.1 1877.26
  5046.6 1876.76  5059.5 1876.76  5060.0 1877.26  5084.7 1878.56  5105.8 1882.12
  5116.3 1882.48  5158.5 1883.51  5200.6 1883.34  5242.8 1884.80  5422.0 1888.72
  5601.2 1891.62  5653.9 1893.39  5664.4 1893.11  5706.6 1894.46  5748.8 1894.94
  5822.5 1897.23  5927.9 1902.33  6043.9 1905.88  6096.6 1908.18  6265.3 1920.49
#Mann=3,-1,0
  4745.4    0.05       0  5046.1    0.03       0  5060.0    0.05       0
Bank Sta=5046.1,5060
Exp/Cntr=0.3,0.1

Type RM Length L Ch R = 1,80634,501,501,501
BEGIN DESCRIPTION:
Spring Creek 134.0
END DESCRIPTION:
XS GIS Cut Line= 3
      1659304.97      6878488.00      1659805.00      6878538.00
      1660535.52      6878254.85
#Sta/Elev= 30
  4503.7 1899.92  4564.0 1896.68  4644.4 1890.82  4664.5 1888.49  4825.3 1882.68
  4895.7 1880.90  4915.8 1877.21  4925.8 1876.77  4939.0 1875.14  4939.5 1874.64
  4952.4 1874.64  4952.9 1875.14  4953.5 1875.81  4966.0 1876.27  4996.2 1875.86
  5003.7 1876.56  5038.4 1876.94  5045.7 1878.54  5059.8 1878.93  5135.5 1880.13
  5154.7 1882.03  5274.4 1883.10  5432.5 1888.24  5516.9 1888.90  5531.7 1887.93
  5585.4 1889.53  5625.9 1889.37  5710.3 1890.43  5764.7 1891.61  5789.7 1892.85
#Mann=3,-1,0
  4503.7    0.05       0  4939.0    0.05       0  4952.9    0.05       0
Bank Sta=4939,4952.9
Exp/Cntr=0.3,0.1

Type RM Length L Ch R = 1,80133,447,447,447
BEGIN DESCRIPTION:
Spring Creek 133.0
END DESCRIPTION:
XS GIS Cut Line= 3
      1659454.99      6879088.00      1659805.00      6879038.00
      1660205.04      6879038.00
#Sta/Elev= 30
  4646.4 1887.33  4727.2 1884.22  4747.4 1882.97  4757.5 1881.56  4797.9 1879.41
  4828.2 1876.48  4858.5 1874.63  4868.6 1874.30  4878.7 1874.77  4898.9 1876.71
  4949.5 1877.09  4969.7 1876.73  4990.1 1866.78  4990.6 1866.28  5004.3 1866.28
  5004.8 1866.78  5010.0 1867.17  5020.0 1870.01  5030.0 1871.94  5050.0 1872.92
  5060.0 1874.12  5080.0 1879.17  5090.0 1880.03  5100.0 1877.96  5150.0 1881.61
  5260.0 1884.18  5270.0 1884.10  5330.0 1885.82  5380.0 1886.61  5400.0 1887.72
#Mann=3,-1,0
  4646.4    0.05       0  4990.1    0.05       0  5004.8    0.05       0
Bank Sta=4990.1,5004.8
Exp/Cntr=0.3,0.1

Type RM Length L Ch R = 1,79686,452,452,452
BEGIN DESCRIPTION:
Spring Creek 132.0
END DESCRIPTION:
XS GIS Cut Line= 3
      1659305.01      6879288.00      1659755.00      6879438.00
      1660254.97      6879537.99
#Sta/Elev= 30
  4520.5 1890.57  4615.4 1887.93  4741.8 1883.48  4794.6 1880.64  4847.3 1876.58
  4878.9 1874.92  4921.0 1871.58  4942.1 1871.17  4973.7 1871.39  4997.4 1870.47
  5005.0 1869.32  5015.2 1866.57  5018.1 1864.51  5018.6 1864.01  5032.3 1864.01
  5032.8 1864.51  5035.6 1864.94  5045.8 1868.28  5056.0 1870.88  5066.2 1871.53
  5086.6 1874.98  5158.0 1877.58  5178.4 1878.94  5290.6 1881.82  5331.4 1883.52
  5372.2 1886.13  5382.4 1887.32  5423.1 1889.60  5484.3 1895.16  5504.7 1896.12
#Mann=3,-1,0
  4520.5    0.05       0  5018.1    0.03       0  5032.8    0.05       0
Bank Sta=5018.1,5032.8
Exp/Cntr=0.3,0.1

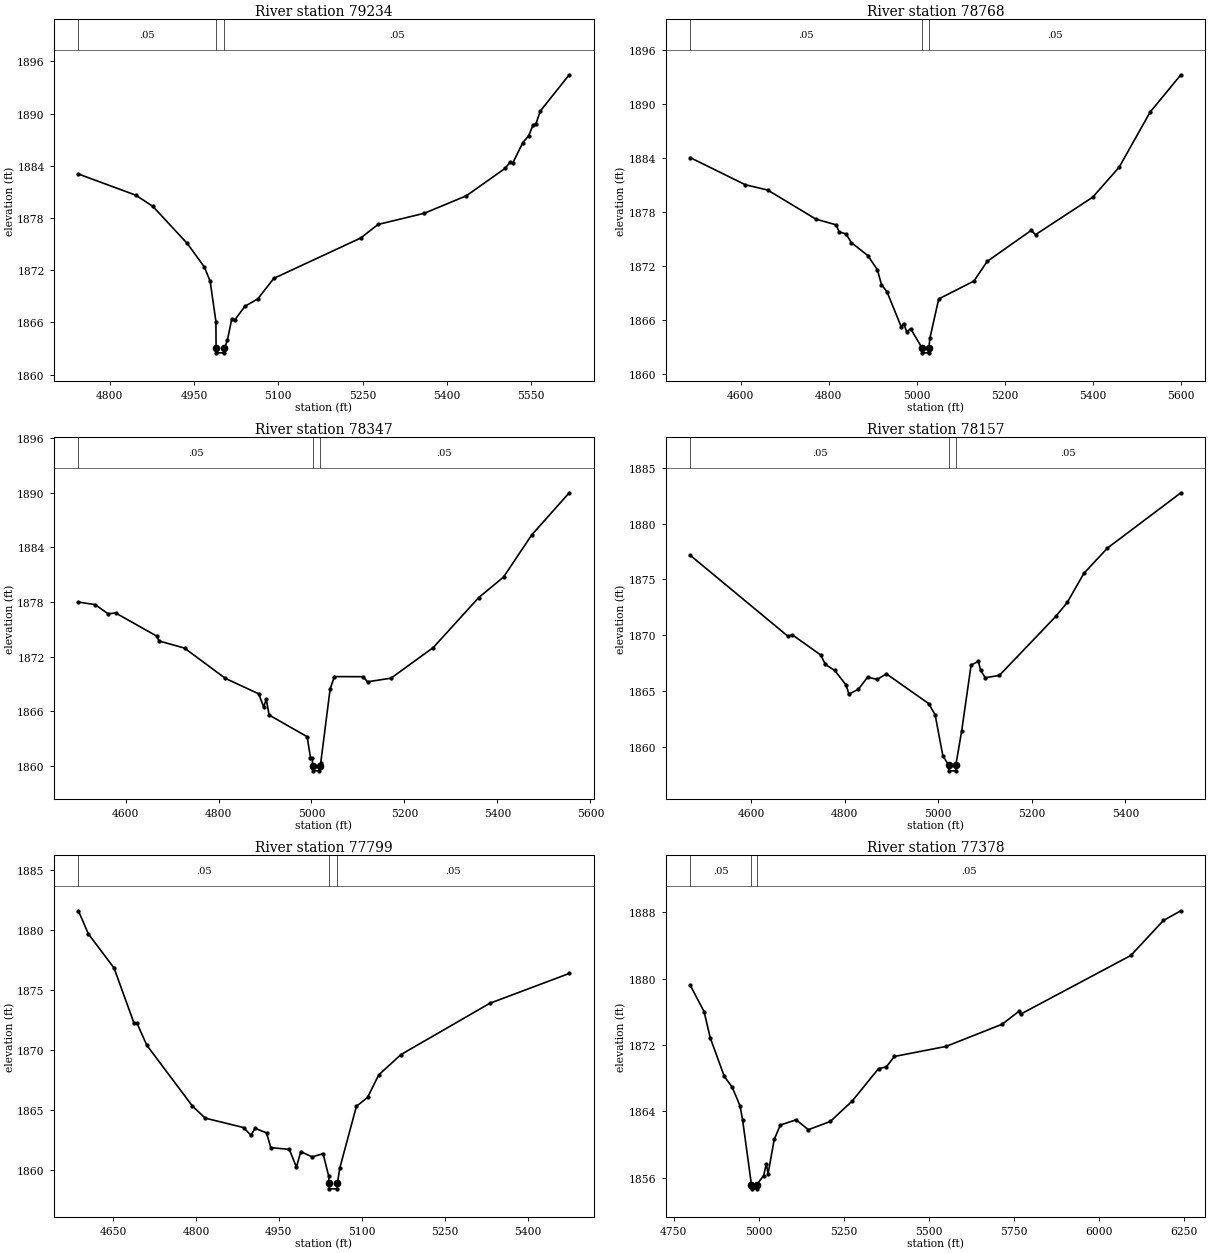
Type RM Length L Ch R = 1,79234,466,466,466
BEGIN DESCRIPTION:
Spring Creek 131.0
END DESCRIPTION:
XS GIS Cut Line= 3
      1659355.03      6879788.01      1659605.00      6879838.00
      1660205.01      6879688.00
#Sta/Elev= 30
  4744.4 1883.06  4846.4 1880.63  4876.9 1879.34  4938.1 1875.08  4968.7 1872.36
  4978.9 1870.72  4989.1 1866.10  4989.4 1863.00  4989.9 1862.50  5003.7 1862.50
  5004.2 1863.00  5009.6 1863.96  5017.4 1866.43  5022.5 1866.27  5040.6 1867.84
  5063.7 1868.71  5092.1 1871.06  5246.7 1875.70  5277.6 1877.26  5360.1 1878.55
  5434.8 1880.56  5504.4 1883.74  5512.1 1884.40  5517.3 1884.32  5535.3 1886.68
  5545.6 1887.46  5553.4 1888.68  5558.5 1888.81  5566.2 1890.29  5617.8 1894.47
#Mann=3,-1,0
  4744.4    0.05       0  4989.4    0.03       0  5004.2    0.05       0
Bank Sta=4989.4,5004.2
Exp/Cntr=0.3,0.1

Type RM Length L Ch R = 1,78768,421,421,421
BEGIN DESCRIPTION:
Spring Creek 130.0
END DESCRIPTION:
XS GIS Cut Line= 3
      1659204.97      6880037.98      1659655.00      6880288.00
      1660254.98      6880288.00
#Sta/Elev= 30
  4484.9 1884.02  4610.8 1880.99  4661.1 1880.41  4770.9 1877.17  4816.7 1876.54
  4823.5 1875.76  4839.6 1875.52  4851.0 1874.57  4888.8 1873.12  4910.5 1871.54
  4919.6 1869.90  4932.2 1869.10  4964.3 1865.23  4970.0 1865.56  4976.8 1864.68
  4986.0 1864.99  5012.3 1862.81  5012.8 1862.31  5026.7 1862.31  5027.2 1862.81
  5029.7 1863.94  5049.7 1868.30  5129.7 1870.29  5159.7 1872.47  5259.7 1875.92
  5269.7 1875.45  5399.7 1879.62  5459.7 1882.96  5529.7 1889.06  5599.7 1893.22
#Mann=3,-1,0
  4484.9    0.05       0  5012.3    0.03       0  5027.2    0.05       0
Bank Sta=5012.3,5027.2
Exp/Cntr=0.3,0.1

Type RM Length L Ch R = 1,78347,190,190,190
BEGIN DESCRIPTION:
Spring Creek 129.0
END DESCRIPTION:
XS GIS Cut Line= 3
      1659212.64      6880473.59      1659657.08      6880709.70
      1660205.05      6880637.99
#Sta/Elev= 30
  4498.6 1878.00  4534.8 1877.71  4562.4 1876.71  4578.7 1876.80  4666.7 1874.27
  4672.3 1873.72  4726.9 1872.94  4814.9 1869.61  4886.5 1867.92  4897.1 1866.48
  4902.8 1867.31  4908.9 1865.59  4990.7 1863.21  4997.9 1860.89  5001.9 1860.89
  5002.3 1859.96  5002.8 1859.46  5016.8 1859.46  5017.3 1859.96  5019.9 1860.32
  5040.1 1868.43  5049.3 1869.81  5110.7 1869.80  5120.8 1869.24  5171.2 1869.64
  5262.0 1873.00  5359.8 1878.49  5413.3 1880.75  5473.8 1885.37  5554.5 1890.00
#Mann=3,-1,0
  4498.6    0.05       0  5002.3    0.03       0  5017.3    0.05       0
Bank Sta=5002.3,5017.3
Exp/Cntr=0.3,0.1

Type RM Length L Ch R = 1,78157,358,358,358
BEGIN DESCRIPTION:
Mapping XS fb312b8a
END DESCRIPTION:
XS GIS Cut Line= 2
      1659077.19      6880827.75      1660121.20      6880938.74
#Sta/Elev= 30
  4468.9 1877.18  4677.9 1869.92  4687.9 1870.03  4748.3 1868.23  4758.3 1867.38
  4778.4 1866.84  4802.9 1865.52  4808.6 1864.72  4828.7 1865.14  4848.8 1866.24
  4869.0 1866.04  4889.1 1866.53  4979.6 1863.86  4993.1 1862.87  5009.7 1859.19
  5022.4 1858.34  5022.9 1857.84  5036.9 1857.84  5037.4 1858.34  5050.0 1861.44
  5070.1 1867.33  5085.6 1867.65  5090.7 1866.84  5100.3 1866.19  5130.4 1866.39
  5251.1 1871.68  5275.8 1872.94  5311.4 1875.55  5361.7 1877.81  5518.8 1882.77
#Mann=3,-1,0
  4468.9    0.05       0  5022.4    0.03       0  5037.4    0.05       0
Bank Sta=5022.4,5037.4
Exp/Cntr=0.3,0.1

Type RM Length L Ch R = 1,77799,421,421,421
BEGIN DESCRIPTION:
Spring Creek 128.0
END DESCRIPTION:
XS GIS Cut Line= 3
      1659055.03      6881088.01      1659455.00      6881188.00
      1659927.88      6881234.00
#Sta/Elev= 30
  4587.6 1881.60  4605.6 1879.67  4652.0 1876.83  4688.1 1872.23  4693.2 1872.25
  4711.3 1870.38  4793.7 1865.31  4816.9 1864.30  4886.5 1863.51  4899.4 1862.87
  4907.1 1863.45  4927.7 1863.07  4935.5 1861.84  4969.0 1861.69  4981.8 1860.21
  4989.6 1861.51  5009.9 1861.07  5030.0 1861.33  5040.1 1859.47  5040.7 1858.90
  5041.2 1858.40  5055.5 1858.40  5056.0 1858.90  5060.2 1860.14  5090.3 1865.29
  5110.4 1866.03  5130.5 1867.90  5170.7 1869.60  5331.4 1873.88  5475.0 1876.37
#Mann=3,-1,0
  4587.6    0.05       0  5040.7    0.03       0  5056.0    0.05       0
Bank Sta=5040.7,5056
Exp/Cntr=0.3,0.1

Type RM Length L Ch R = 1,77378,206,206,206
BEGIN DESCRIPTION:
Spring Creek 127.0
END DESCRIPTION:
XS GIS Cut Line= 3
      1659004.95      6881437.99      1659205.00      6881488.00
      1660404.97      6881188.01
#Sta/Elev= 30
  4798.3 1879.24  4839.6 1876.02  4857.6 1872.88  4898.8 1868.24  4922.0 1866.94
  4945.2 1864.70  4953.0 1862.93  4978.8 1855.19  4979.3 1854.69  4993.7 1854.69
  4994.2 1855.19  5014.8 1856.29  5022.5 1857.72  5027.7 1856.48  5045.7 1860.63
  5063.8 1862.37  5110.2 1863.00  5146.2 1861.81  5210.7 1862.80  5275.1 1865.26
  5352.4 1869.16  5375.6 1869.37  5398.8 1870.62  5550.8 1871.83  5715.7 1874.50
  5764.7 1876.04  5769.9 1875.71  6094.6 1882.79  6189.9 1886.99  6241.4 1888.16
#Mann=3,-1,0
  4798.3    0.05       0  4978.8    0.05       0  4994.2    0.05       0
Bank Sta=4978.8,4994.2
Exp/Cntr=0.3,0.1

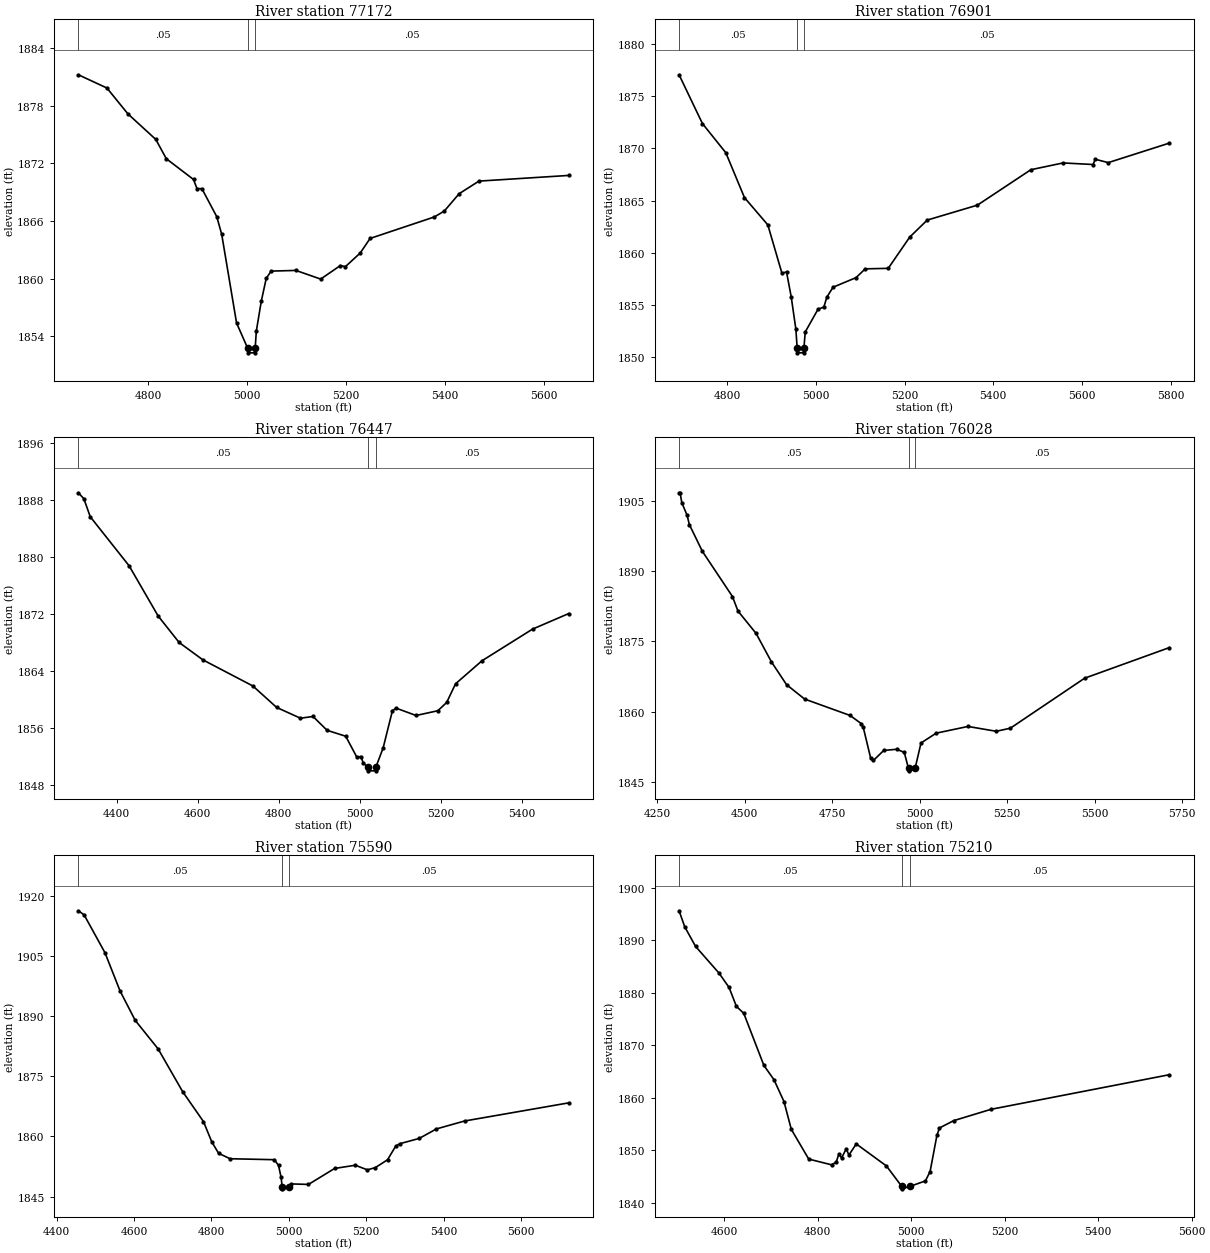
Type RM Length L Ch R = 1,77172,271,271,271
BEGIN DESCRIPTION:
Mapping XS 4a3d99d9
END DESCRIPTION:
XS GIS Cut Line= 3
      1658886.22      6881515.23      1659045.97      6881681.92
      1659806.38      6881654.15
#Sta/Elev= 30
  4658.8 1881.23  4716.6 1879.85  4759.0 1877.16  4815.4 1874.50  4836.7 1872.49
  4891.7 1870.33  4898.7 1869.38  4908.7 1869.37  4938.7 1866.46  4948.7 1864.63
  4978.8 1855.39  5001.1 1852.78  5001.6 1852.28  5016.0 1852.28  5016.5 1852.78
  5018.8 1854.55  5028.8 1857.65  5038.8 1860.03  5048.8 1860.79  5098.8 1860.86
  5148.9 1859.96  5188.9 1861.37  5198.9 1861.25  5228.9 1862.67  5248.9 1864.19
  5379.0 1866.43  5399.0 1867.04  5429.1 1868.85  5469.1 1870.16  5650.6 1870.75
#Mann=3,-1,0
  4658.8    0.05       0  5001.1    0.05       0  5016.5    0.05       0
Bank Sta=5001.1,5016.5
Exp/Cntr=0.3,0.1

Type RM Length L Ch R = 1,76901,454,454,454
BEGIN DESCRIPTION:
Spring Creek 126.0
END DESCRIPTION:
XS GIS Cut Line= 3
      1658905.05      6881838.02      1659205.00      6881938.00
      1659966.13      6881727.06
#Sta/Elev= 30
  4691.4 1877.05  4744.1 1872.38  4796.8 1869.59  4838.9 1865.29  4891.6 1862.68
  4923.3 1858.07  4933.8 1858.17  4944.3 1855.81  4954.9 1852.68  4957.7 1850.93
  4958.2 1850.43  4972.6 1850.43  4973.1 1850.93  4976.0 1852.43  5004.9 1854.61
  5018.0 1854.81  5024.7 1855.76  5038.7 1856.71  5090.6 1857.63  5111.3 1858.47
  5163.2 1858.52  5211.7 1861.51  5251.2 1863.14  5364.4 1864.57  5484.9 1867.96
  5557.6 1868.61  5625.2 1868.46  5630.4 1868.96  5659.5 1868.64  5797.4 1870.51
#Mann=3,-1,0
  4691.4    0.05       0  4957.7    0.03       0  4973.1    0.05       0
Bank Sta=4957.7,4973.1
Exp/Cntr=0.3,0.1

Type RM Length L Ch R = 1,76447,419,419,419
BEGIN DESCRIPTION:
Spring Creek 125.0
END DESCRIPTION:
XS GIS Cut Line= 3
      1658655.02      6881988.01      1659255.00      6882338.00
      1659705.02      6882588.01
#Sta/Elev= 30
  4305.6 1888.97  4319.2 1888.13  4334.9 1885.61  4430.9 1878.72  4502.4 1871.69
  4554.1 1867.98  4612.8 1865.54  4736.0 1861.88  4794.7 1858.87  4853.4 1857.36
  4884.4 1857.60  4919.2 1855.66  4965.1 1854.83  4992.3 1851.91  5003.1 1851.98
  5008.2 1851.05  5020.6 1850.48  5021.1 1849.98  5038.8 1849.98  5039.3 1850.48
  5057.4 1853.20  5080.3 1858.42  5089.4 1858.77  5138.6 1857.74  5192.4 1858.41
  5214.1 1859.57  5235.9 1862.18  5301.1 1865.41  5425.8 1869.85  5515.0 1872.03
#Mann=3,-1,0
  4305.6    0.05       0  5020.6    0.03       0  5039.3    0.05       0
Bank Sta=5020.6,5039.3
Exp/Cntr=0.3,0.1

Type RM Length L Ch R = 1,76028,438,438,438
BEGIN DESCRIPTION:
Spring Creek 124.0
END DESCRIPTION:
XS GIS Cut Line= 3
      1658405.01      6882288.01      1659005.00      6882638.00
      1659704.98      6882738.00
#Sta/Elev= 30
  4312.1 1906.70  4315.0 1906.70  4319.9 1904.60  4335.2 1901.86  4341.4 1899.93
  4378.7 1894.22  4464.7 1884.59  4480.4 1881.50  4532.1 1876.74  4576.3 1870.64
  4619.3 1865.80  4671.0 1862.73  4801.2 1859.23  4832.6 1857.51  4838.4 1856.78
  4859.9 1850.12  4867.8 1849.65  4897.1 1851.77  4934.4 1852.03  4955.9 1851.36
  4968.0 1847.93  4968.5 1847.43  4986.7 1847.93  5003.8 1853.37  5047.1 1855.46
  5138.0 1856.89  5218.8 1855.86  5259.2 1856.52  5471.4 1867.17  5713.8 1873.70
#Mann=3,-1,0
  4312.1    0.05       0  4968.0    0.03       0  4986.7    0.05       0
Bank Sta=4968,4986.7
Exp/Cntr=0.3,0.1

Type RM Length L Ch R = 1,75590,380,380,380
BEGIN DESCRIPTION:
Spring Creek 123.0
END DESCRIPTION:
XS GIS Cut Line= 3
      1658204.97      6882687.99      1658705.00      6882888.00
      1659405.04      6883088.01
#Sta/Elev= 30
  4456.4 1916.20  4471.2 1915.19  4525.1 1905.75  4564.1 1896.22  4603.2 1888.90
  4662.4 1881.79  4725.7 1871.15  4779.5 1863.69  4801.1 1858.61  4818.6 1855.78
  4848.2 1854.42  4962.6 1854.18  4973.4 1852.77  4980.1 1849.78  4982.9 1847.42
  4983.4 1846.92  5001.6 1847.42  5005.3 1848.15  5050.8 1848.02  5118.4 1852.00
  5171.7 1852.80  5203.0 1851.65  5223.8 1852.22  5255.0 1854.16  5275.8 1857.50
  5286.2 1858.15  5336.9 1859.48  5381.1 1861.84  5453.9 1863.82  5723.0 1868.34
#Mann=3,-1,0
  4456.4    0.05       0  4982.9    0.03       0  5001.6    0.05       0
Bank Sta=4982.9,5001.6
Exp/Cntr=0.3,0.1

Type RM Length L Ch R = 1,75210,168,168,168
BEGIN DESCRIPTION:
Spring Creek 122.0
END DESCRIPTION:
XS GIS Cut Line= 3
      1658174.46      6882990.96      1658598.06      6883237.48
      1659154.96      6883288.00
#Sta/Elev= 30
  4503.0 1895.60  4515.2 1892.53  4538.3 1888.81  4588.5 1883.72  4610.0 1880.99
  4625.7 1877.38  4641.5 1876.05  4684.5 1866.13  4706.0 1863.42  4727.5 1859.25
  4743.2 1853.94  4780.5 1848.28  4829.3 1847.19  4839.2 1847.69  4845.0 1849.24
  4850.8 1848.50  4860.7 1850.23  4866.5 1849.05  4882.2 1851.17  4946.8 1846.97
  4979.3 1843.11  4979.8 1842.61  4998.1 1843.11  5030.2 1844.12  5040.2 1845.90
  5054.8 1852.79  5060.3 1854.21  5090.5 1855.60  5170.8 1857.77  5552.3 1864.36
#Mann=3,-1,0
  4503.0    0.05       0  4979.3    0.03       0  4998.1    0.05       0
Bank Sta=4979.3,4998.1
Exp/Cntr=0.3,0.1

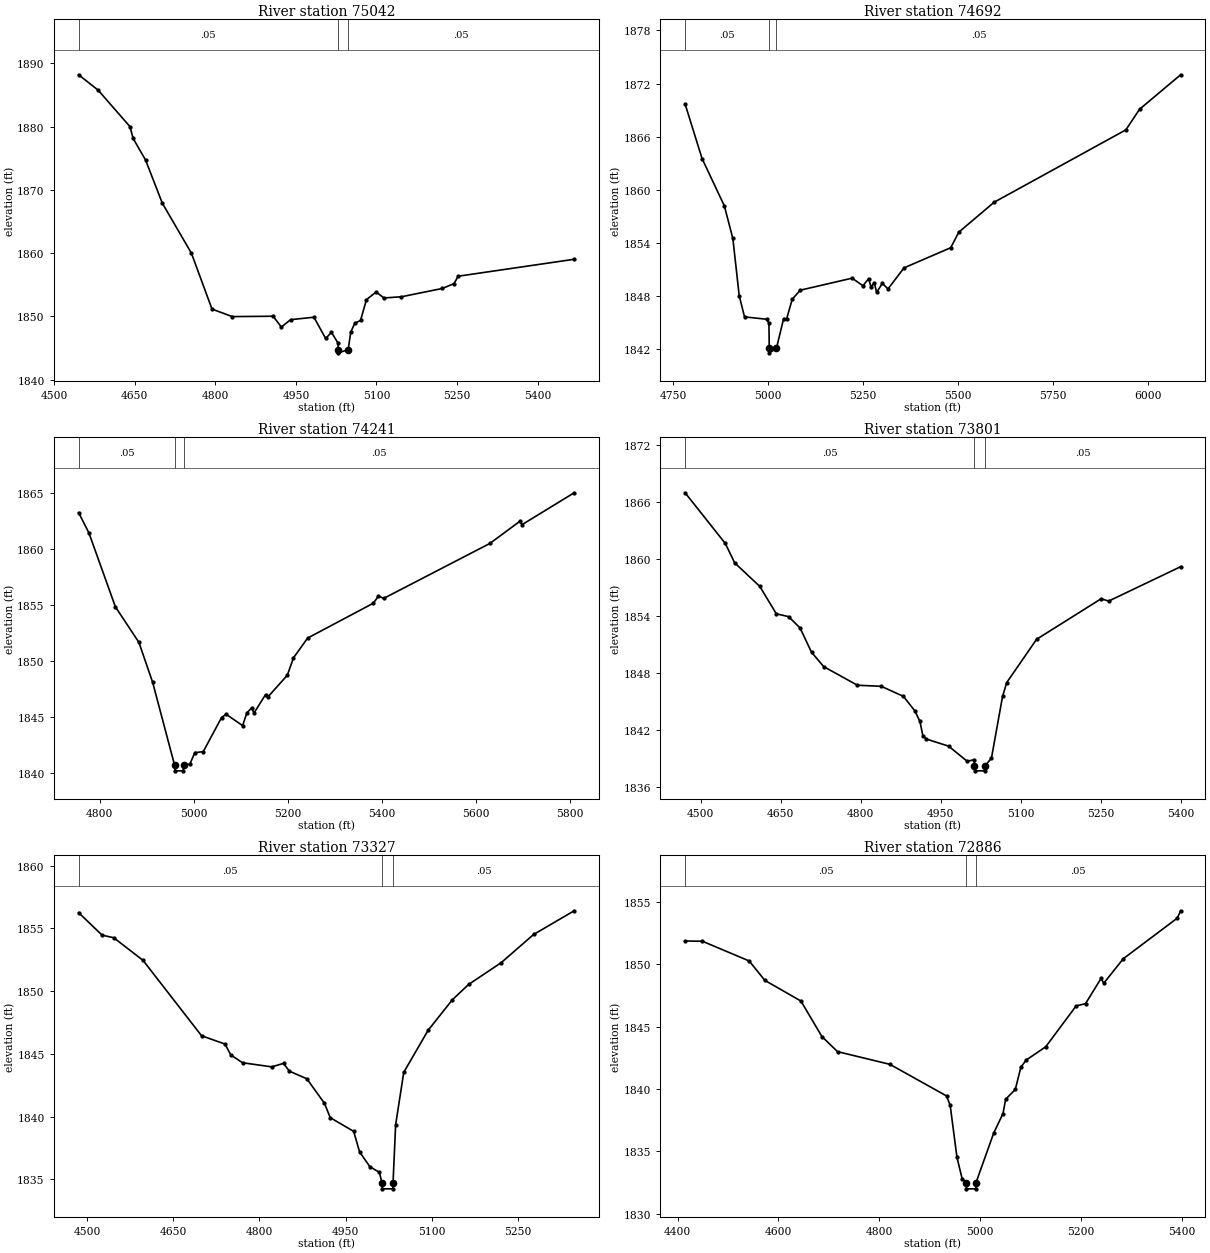
Type RM Length L Ch R = 1,75042,350,350,350
BEGIN DESCRIPTION:
Mapping XS 525cef45
END DESCRIPTION:
XS GIS Cut Line= 2
      1658101.56      6883195.83      1658951.09      6883556.44
#Sta/Elev= 30
  4545.3 1888.21  4581.6 1885.78  4640.9 1880.01  4646.8 1878.14  4670.0 1874.72
  4701.1 1867.91  4755.4 1859.98  4793.7 1851.15  4831.5 1849.96  4907.5 1850.02
  4922.9 1848.31  4940.1 1849.48  4983.6 1849.86  5005.3 1846.50  5016.2 1847.47
  5028.4 1845.77  5028.5 1844.73  5029.0 1844.23  5047.3 1844.73  5052.1 1847.52
  5059.6 1848.90  5070.3 1849.35  5081.4 1852.65  5099.4 1853.85  5113.9 1852.91
  5146.5 1853.10  5222.6 1854.41  5244.3 1855.17  5252.2 1856.35  5468.2 1859.03
#Mann=3,-1,0
  4545.3    0.05       0  5028.5    0.03       0  5047.3    0.05       0
Bank Sta=5028.5,5047.3
Exp/Cntr=0.3,0.1

Type RM Length L Ch R = 1,74692,451,451,451
BEGIN DESCRIPTION:
Spring Creek 121.0
END DESCRIPTION:
XS GIS Cut Line= 3
      1658105.01      6883538.01      1658305.00      6883638.00
      1659205.03      6884238.02
#Sta/Elev= 30
  4781.8 1869.69  4826.5 1863.53  4885.2 1858.19  4907.6 1854.51  4924.3 1848.06
  4938.3 1845.66  4997.0 1845.39  5002.6 1844.94  5003.5 1842.10  5004.0 1841.60
  5022.3 1842.10  5041.4 1845.47  5049.0 1845.40  5064.0 1847.65  5085.0 1848.67
  5221.7 1850.03  5250.3 1849.17  5265.3 1849.98  5271.3 1849.06  5280.3 1849.48
  5286.3 1848.43  5301.3 1849.43  5316.4 1848.82  5358.4 1851.19  5481.6 1853.47
  5502.7 1855.22  5595.8 1858.60  5942.8 1866.77  5978.9 1869.10  6087.1 1872.99
#Mann=3,-1,0
  4781.8    0.05       0  5003.5    0.03       0  5022.3    0.05       0
Bank Sta=5003.5,5022.3
Exp/Cntr=0.3,0.1

Type RM Length L Ch R = 1,74241,440,440,440
BEGIN DESCRIPTION:
Spring Creek 120.0
END DESCRIPTION:
XS GIS Cut Line= 3
      1657955.00      6883888.00      1658155.00      6884038.00
      1658901.78      6884333.98
#Sta/Elev= 30
  4754.9 1863.24  4776.8 1861.43  4833.0 1854.85  4883.0 1851.68  4912.2 1848.12
  4958.9 1840.73  4959.4 1840.23  4977.5 1840.23  4978.0 1840.73  4991.4 1840.83
  5001.8 1841.85  5019.8 1841.94  5058.7 1844.98  5068.4 1845.27  5103.5 1844.26
  5112.5 1845.40  5122.4 1845.82  5127.8 1845.39  5152.1 1847.02  5157.5 1846.83
  5198.5 1848.75  5211.6 1850.30  5241.6 1852.06  5381.4 1855.17  5392.1 1855.80
  5403.4 1855.60  5628.8 1860.49  5692.5 1862.46  5697.8 1862.18  5808.2 1865.01
#Mann=3,-1,0
  4754.9    0.05       0  4958.9    0.03       0  4978.0    0.05       0
Bank Sta=4958.9,4978
Exp/Cntr=0.3,0.1

Type RM Length L Ch R = 1,73801,474,474,474
BEGIN DESCRIPTION:
Spring Creek 119.0
END DESCRIPTION:
XS GIS Cut Line= 3
      1657804.99      6883937.96      1658005.00      6884438.00
      1658255.02      6884738.03
#Sta/Elev= 30
  4470.7 1866.97  4546.1 1861.63  4563.6 1859.59  4610.8 1857.10  4641.7 1854.22
  4664.6 1853.92  4686.1 1852.74  4707.7 1850.17  4730.6 1848.65  4793.8 1846.69
  4838.3 1846.58  4880.0 1845.52  4901.6 1843.98  4911.0 1842.87  4916.4 1841.39
  4923.1 1841.02  4964.8 1840.27  4999.8 1838.67  5012.5 1838.85  5013.3 1838.17
  5013.8 1837.67  5032.1 1837.67  5032.6 1838.17  5045.1 1839.01  5065.9 1845.51
  5073.7 1846.97  5129.7 1851.53  5250.7 1855.80  5265.0 1855.56  5399.8 1859.18
#Mann=3,-1,0
  4470.7    0.05       0  5013.3    0.05       0  5032.6    0.05       0
Bank Sta=5013.3,5032.6
Exp/Cntr=0.3,0.1

Type RM Length L Ch R = 1,73327,441,441,441
BEGIN DESCRIPTION:
Spring Creek 118.0
END DESCRIPTION:
XS GIS Cut Line= 3
      1657555.00      6884237.98      1657655.00      6884738.00
      1657905.01      6884988.01
#Sta/Elev= 30
  4484.9 1856.26  4525.7 1854.47  4546.1 1854.26  4597.1 1852.46  4699.1 1846.45
  4739.9 1845.79  4750.1 1844.92  4770.5 1844.30  4821.5 1843.97  4841.9 1844.25
  4852.1 1843.63  4882.6 1843.02  4913.2 1841.07  4923.4 1839.92  4964.2 1838.83
  4974.4 1837.20  4992.3 1836.02  5009.0 1835.56  5013.4 1834.75  5013.9 1834.25
  5032.3 1834.25  5032.8 1834.75  5037.3 1839.35  5051.4 1843.53  5093.8 1846.88
  5136.2 1849.32  5164.5 1850.54  5221.1 1852.27  5277.7 1854.52  5348.4 1856.41
#Mann=3,-1,0
  4484.9    0.05       0  5013.4    0.05       0  5032.8    0.05       0
Bank Sta=5013.4,5032.8
Exp/Cntr=0.3,0.1

Type RM Length L Ch R = 1,72886,418,418,418
BEGIN DESCRIPTION:
Spring Creek 117.0
END DESCRIPTION:
XS GIS Cut Line= 3
      1657164.03      6884414.58      1657305.00      6884988.00
      1657444.78      6885354.24
#Sta/Elev= 30
  4415.0 1851.85  4449.4 1851.83  4542.1 1850.25  4573.0 1848.70  4644.7 1847.04
  4686.2 1844.20  4717.2 1842.99  4821.1 1841.97  4933.4 1839.44  4940.6 1838.68
  4954.0 1834.53  4964.3 1832.80  4972.4 1832.50  4972.9 1832.00  4991.3 1832.00
  4991.8 1832.50  5026.9 1836.47  5045.3 1838.03  5050.6 1839.18  5069.7 1839.96
  5080.7 1841.74  5091.1 1842.31  5130.1 1843.38  5190.3 1846.65  5208.9 1846.83
  5239.7 1848.85  5245.1 1848.47  5283.8 1850.43  5390.8 1853.68  5397.5 1854.27
#Mann=3,-1,0
  4415.0    0.05       0  4972.4    0.03       0  4991.8    0.05       0
Bank Sta=4972.4,4991.8
Exp/Cntr=0.3,0.1