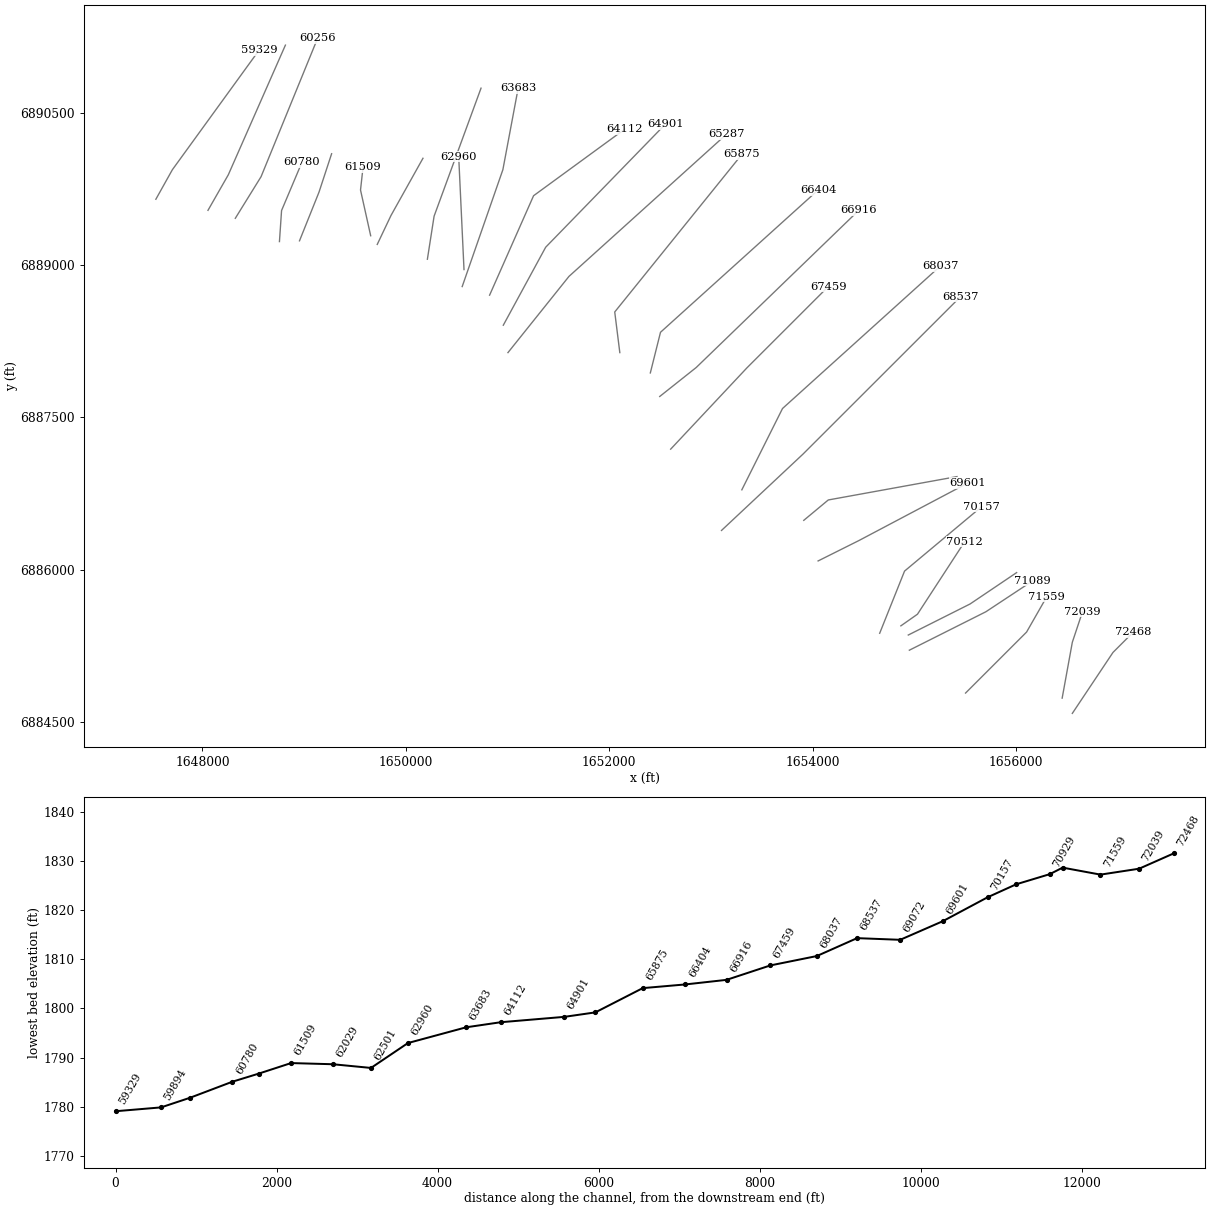
HEC-RAS study Spring Creek.prj: Spring Creek Base Level Engineering

--- Spring Creek.g01 (geometry) --- (continued)

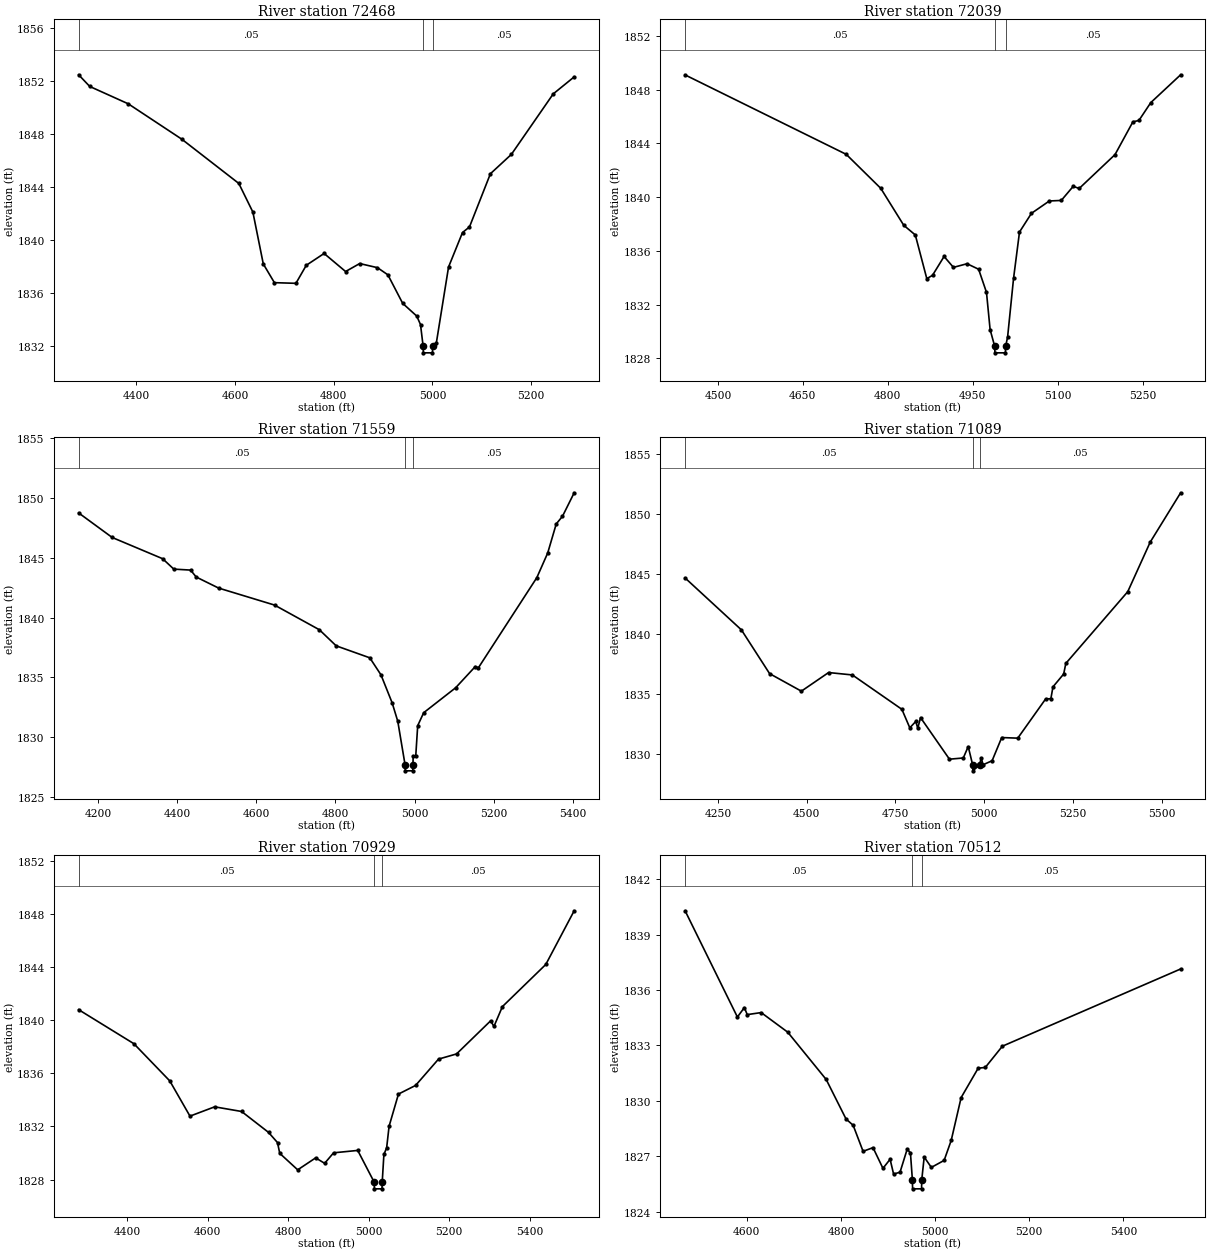
Type RM Length L Ch R = 1,72468,429,429,429
BEGIN DESCRIPTION:
Spring Creek 116.0
END DESCRIPTION:
XS GIS Cut Line= 3
      1656555.01      6884588.01      1656955.00      6885188.00
      1657154.97      6885387.97
#Sta/Elev= 30
  4283.3 1852.48  4305.8 1851.60  4383.9 1850.29  4492.1 1847.63  4607.8 1844.29
  4636.3 1842.13  4657.4 1838.22  4679.9 1836.81  4723.5 1836.76  4744.5 1838.12
  4780.6 1839.01  4824.1 1837.65  4852.7 1838.25  4888.7 1837.94  4909.8 1837.40
  4939.8 1835.25  4968.3 1834.29  4975.9 1833.65  4981.2 1832.02  4981.7 1831.52
  5000.1 1831.52  5000.6 1832.02  5007.9 1832.25  5032.7 1837.99  5061.0 1840.59
  5075.1 1841.01  5117.5 1845.02  5160.0 1846.48  5244.8 1851.04  5287.2 1852.32
#Mann=3,-1,0
  4283.3    0.05       0  4981.2    0.03       0  5000.6    0.05       0
Bank Sta=4981.2,5000.6
Exp/Cntr=0.3,0.1

Type RM Length L Ch R = 1,72039,480,480,480
BEGIN DESCRIPTION:
Spring Creek 115.0
END DESCRIPTION:
XS GIS Cut Line= 3
      1656455.00      6884738.00      1656555.00      6885288.00
      1656654.99      6885587.96
#Sta/Elev= 30
  4442.1 1849.09  4726.7 1843.18  4787.7 1840.65  4828.3 1837.90  4848.7 1837.18
  4869.0 1833.93  4879.1 1834.18  4899.5 1835.58  4916.0 1834.77  4940.1 1835.04
  4960.5 1834.63  4974.4 1832.91  4980.8 1830.14  4988.8 1828.91  4989.3 1828.41
  5007.8 1828.41  5008.3 1828.91  5011.7 1829.59  5022.2 1833.95  5032.7 1837.40
  5053.8 1838.79  5085.4 1839.71  5106.5 1839.75  5127.6 1840.80  5138.1 1840.64
  5201.4 1843.16  5233.0 1845.60  5243.6 1845.70  5264.6 1847.03  5317.3 1849.10
#Mann=3,-1,0
  4442.1    0.05       0  4988.8    0.03       0  5008.3    0.05       0
Bank Sta=4988.8,5008.3
Exp/Cntr=0.3,0.1

Type RM Length L Ch R = 1,71559,470,470,470
BEGIN DESCRIPTION:
Spring Creek 114.0
END DESCRIPTION:
XS GIS Cut Line= 3
      1655505.02      6884788.02      1656105.00      6885388.00
      1656304.99      6885737.99
#Sta/Elev= 30
  4151.5 1848.73  4236.3 1846.68  4363.6 1844.91  4391.9 1844.04  4434.3 1843.96
  4448.5 1843.38  4505.0 1842.46  4646.4 1841.04  4759.6 1838.98  4802.0 1837.64
  4886.9 1836.64  4915.1 1835.22  4943.4 1832.88  4957.6 1831.34  4976.0 1827.71
  4976.5 1827.21  4995.3 1827.21  4995.8 1827.71  4996.5 1828.41  5002.9 1828.41
  5007.9 1830.98  5023.0 1832.06  5103.7 1834.14  5153.3 1835.91  5161.2 1835.81
  5308.8 1843.33  5336.2 1845.38  5357.8 1847.81  5373.6 1848.45  5403.1 1850.41
#Mann=3,-1,0
  4151.5    0.05       0  4976.0    0.03       0  4995.8    0.05       0
Bank Sta=4976,4995.8
Exp/Cntr=0.3,0.1

Type RM Length L Ch R = 1,71089,160,160,160
BEGIN DESCRIPTION:
Spring Creek 113.0
END DESCRIPTION:
XS GIS Cut Line= 3
      1654952.26      6885209.72      1655705.00      6885588.00
      1656166.95      6885893.36
#Sta/Elev= 30
  4157.5 1844.68  4316.2 1840.36  4395.6 1836.72  4485.1 1835.26  4561.8 1836.81
  4628.8 1836.61  4768.3 1833.75  4790.6 1832.21  4807.4 1832.74  4813.0 1832.18
  4820.9 1833.06  4902.3 1829.60  4941.3 1829.70  4955.2 1830.65  4967.7 1829.13
  4968.2 1828.63  4987.5 1829.13  4991.6 1829.71  4997.2 1829.14  5022.5 1829.47
  5049.6 1831.40  5094.8 1831.35  5173.0 1834.60  5188.1 1834.64  5194.0 1835.62
  5224.2 1836.69  5230.2 1837.57  5404.7 1843.54  5467.9 1847.66  5553.7 1851.77
#Mann=3,-1,0
  4157.5    0.05       0  4967.7    0.03       0  4987.5    0.05       0
Bank Sta=4967.7,4987.5
Exp/Cntr=0.3,0.1

Type RM Length L Ch R = 1,70929,417,417,417
BEGIN DESCRIPTION:
Spring Creek 112.0
END DESCRIPTION:
XS GIS Cut Line= 3
      1654941.77      6885358.99      1655549.44      6885664.56
      1656007.32      6885973.28
#Sta/Elev= 30
  4278.7 1840.78  4416.1 1838.22  4505.4 1835.42  4555.6 1832.77  4617.0 1833.47
  4684.0 1833.12  4750.9 1831.55  4773.3 1830.78  4778.9 1829.97  4823.5 1828.73
  4868.2 1829.63  4890.5 1829.22  4912.8 1830.01  4972.8 1830.19  5013.8 1827.80
  5014.3 1827.30  5033.2 1827.30  5033.7 1827.80  5037.9 1829.89  5044.7 1830.38
  5050.8 1832.01  5074.1 1834.43  5116.7 1835.08  5173.7 1837.06  5218.6 1837.45
  5303.3 1839.94  5311.6 1839.52  5332.6 1841.01  5440.5 1844.18  5511.1 1848.22
#Mann=3,-1,0
  4278.7    0.05       0  5013.8    0.03       0  5033.7    0.05       0
Bank Sta=5013.8,5033.7
Exp/Cntr=0.3,0.1

Type RM Length L Ch R = 1,70512,355,355,355
BEGIN DESCRIPTION:
Mapping XS 42e02b95
END DESCRIPTION:
XS GIS Cut Line= 3
      1654868.91      6885449.30      1655032.08      6885563.87
      1655497.38      6886279.17
#Sta/Elev= 30
  4469.0 1840.29  4580.1 1834.54  4594.9 1835.05  4601.0 1834.67  4630.6 1834.78
  4687.0 1833.72  4768.7 1831.16  4810.9 1829.02  4826.0 1828.68  4847.1 1827.27
  4868.2 1827.47  4889.3 1826.35  4904.5 1826.84  4911.9 1826.04  4925.6 1826.14
  4940.7 1827.38  4947.7 1827.19  4951.8 1825.74  4952.3 1825.24  4971.3 1825.24
  4971.8 1825.74  4976.9 1826.96  4992.1 1826.40  5019.3 1826.78  5034.3 1827.86
  5055.4 1830.18  5091.6 1831.77  5106.7 1831.81  5143.0 1832.96  5521.7 1837.14
#Mann=3,-1,0
  4469.0    0.05       0  4951.8    0.03       0  4971.8    0.05       0
Bank Sta=4951.8,4971.8
Exp/Cntr=0.3,0.1

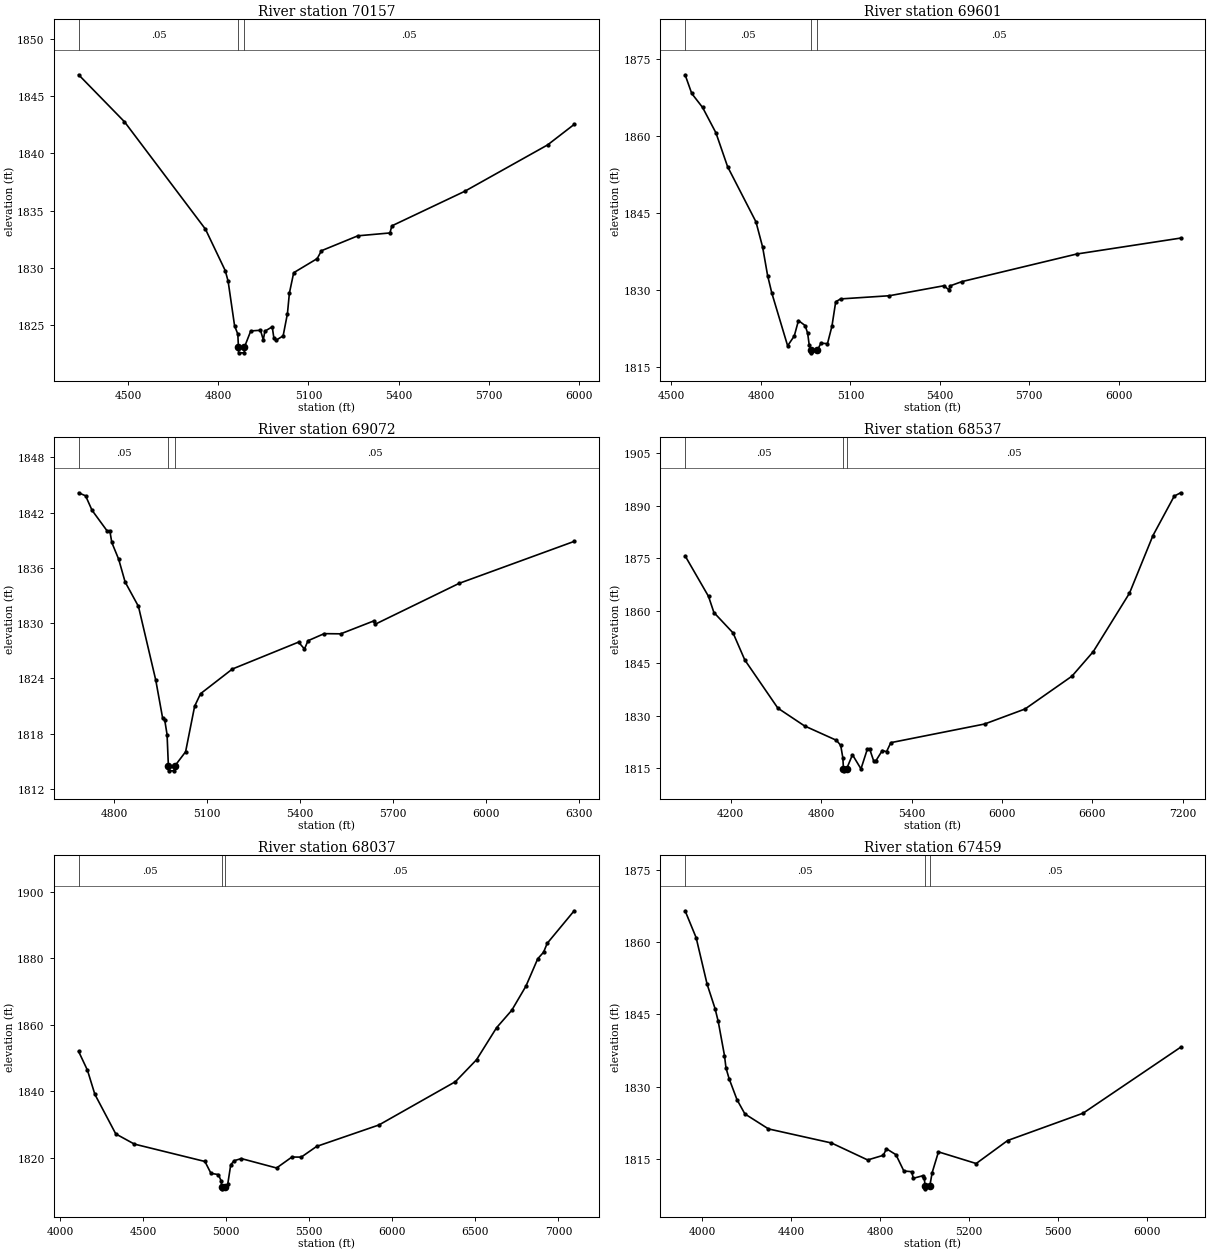
Type RM Length L Ch R = 1,70157,556,556,556
BEGIN DESCRIPTION:
Spring Creek 111.0
END DESCRIPTION:
XS GIS Cut Line= 3
      1654660.55      6885376.35      1654905.00      6885988.00
      1655664.00      6886622.87
#Sta/Elev= 30
  4335.6 1846.86  4488.1 1842.76  4757.4 1833.39  4823.3 1829.77  4832.8 1828.85
  4854.3 1824.96  4865.1 1824.23  4867.1 1823.10  4867.6 1822.60  4886.6 1822.60
  4887.1 1823.10  4908.1 1824.51  4940.4 1824.57  4949.8 1823.74  4955.2 1824.49
  4979.5 1824.87  4984.9 1823.91  4991.6 1823.69  5015.8 1824.08  5030.1 1826.02
  5036.6 1827.81  5050.9 1829.59  5129.0 1830.82  5143.3 1831.51  5264.3 1832.81
  5371.0 1833.06  5377.5 1833.68  5619.5 1836.69  5895.4 1840.74  5983.8 1842.53
#Mann=3,-1,0
  4335.6    0.05       0  4867.1    0.05       0  4887.1    0.05       0
Bank Sta=4867.1,4887.1
Exp/Cntr=0.3,0.1

Type RM Length L Ch R = 1,69601,529,529,529
BEGIN DESCRIPTION:
Spring Creek 110.0
END DESCRIPTION:
XS GIS Cut Line= 3
      1654055.02      6886088.01      1654455.00      6886288.00
      1655528.63      6886855.54
#Sta/Elev= 30
  4545.8 1871.99  4568.1 1868.34  4604.5 1865.61  4649.2 1860.66  4688.3 1854.06
  4783.4 1843.30  4805.7 1838.39  4822.5 1832.81  4836.5 1829.42  4889.6 1819.11
  4911.9 1821.03  4925.9 1824.04  4948.3 1823.06  4956.7 1821.57  4962.2 1819.19
  4969.0 1818.24  4969.5 1817.74  4989.1 1818.24  5001.2 1819.62  5023.2 1819.54
  5038.2 1822.94  5050.8 1827.70  5067.2 1828.26  5230.5 1828.88  5413.7 1830.83
  5430.1 1830.04  5435.7 1830.83  5474.1 1831.64  5858.9 1837.02  6207.4 1840.13
#Mann=3,-1,0
  4545.8    0.05       0  4969.0    0.03       0  4989.1    0.05       0
Bank Sta=4969,4989.1
Exp/Cntr=0.3,0.1

Type RM Length L Ch R = 1,69072,535,535,535
BEGIN DESCRIPTION:
Spring Creek 109.0
END DESCRIPTION:
XS GIS Cut Line= 3
      1653914.03      6886487.48      1654155.00      6886688.00
      1655420.49      6886917.95
#Sta/Elev= 30
  4685.7 1844.16  4708.2 1843.83  4729.0 1842.26  4778.5 1839.98  4786.3 1840.05
  4792.8 1838.76  4815.0 1836.94  4835.8 1834.47  4878.8 1831.82  4934.7 1823.81
  4956.9 1819.68  4963.4 1819.52  4971.2 1817.90  4975.5 1814.46  4976.0 1813.96
  4995.1 1813.96  4995.6 1814.46  5031.0 1816.03  5060.2 1820.98  5079.3 1822.34
  5182.1 1825.02  5395.6 1827.94  5414.8 1827.19  5426.1 1828.09  5478.3 1828.86
  5531.7 1828.84  5638.4 1830.24  5643.5 1829.89  5913.9 1834.32  6285.4 1838.88
#Mann=3,-1,0
  4685.7    0.05       0  4975.5    0.05       0  4995.6    0.05       0
Bank Sta=4975.5,4995.6
Exp/Cntr=0.3,0.1

Type RM Length L Ch R = 1,68537,500,500,500
BEGIN DESCRIPTION:
Spring Creek 108.0
END DESCRIPTION:
XS GIS Cut Line= 3
      1653105.03      6886388.03      1653905.00      6887138.00
      1655455.02      6888688.02
#Sta/Elev= 30
  3897.1 1875.65  4052.6 1864.07  4088.3 1859.47  4215.3 1853.66  4293.4 1845.93
  4512.7 1832.19  4689.6 1827.12  4901.6 1823.01  4929.9 1821.55  4944.1 1817.96
  4948.1 1814.80  4948.6 1814.30  4968.3 1814.80  5007.8 1818.89  5064.3 1814.86
  5106.8 1820.53  5120.9 1820.65  5149.2 1817.06  5163.3 1817.17  5205.8 1820.10
  5234.1 1819.78  5262.3 1822.34  5884.6 1827.66  6153.3 1831.95  6464.4 1841.31
  6605.8 1848.31  6846.3 1865.00  7001.8 1881.42  7143.2 1892.69  7185.7 1893.64
#Mann=3,-1,0
  3897.1    0.05       0  4948.1    0.03       0  4968.3    0.05       0
Bank Sta=4948.1,4968.3
Exp/Cntr=0.3,0.1

Type RM Length L Ch R = 1,68037,578,578,578
BEGIN DESCRIPTION:
Spring Creek 107.0
END DESCRIPTION:
XS GIS Cut Line= 3
      1653304.99      6886787.98      1653705.00      6887588.00
      1655254.99      6888987.99
#Sta/Elev= 30
  4111.7 1851.97  4164.8 1846.33  4209.5 1839.07  4335.3 1827.18  4447.1 1824.12
  4872.0 1818.89  4908.3 1815.32  4953.0 1814.95  4969.8 1813.02  4973.4 1811.16
  4973.9 1810.66  4994.2 1811.16  5009.5 1812.12  5027.4 1817.91  5048.4 1819.13
  5091.0 1819.76  5303.2 1816.93  5395.8 1820.23  5451.9 1820.20  5544.6 1823.42
  5919.7 1829.87  6380.0 1842.89  6507.1 1849.49  6627.4 1859.10  6719.3 1864.37
  6804.5 1871.63  6875.5 1879.85  6910.6 1881.82  6932.3 1884.48  7094.8 1894.28
#Mann=3,-1,0
  4111.7    0.05       0  4973.4    0.03       0  4994.2    0.05       0
Bank Sta=4973.4,4994.2
Exp/Cntr=0.3,0.1

Type RM Length L Ch R = 1,67459,543,543,543
BEGIN DESCRIPTION:
Spring Creek 106.0
END DESCRIPTION:
XS GIS Cut Line= 3
      1652604.97      6887187.97      1653355.00      6887988.00
      1654155.00      6888788.00
#Sta/Elev= 30
  3923.8 1866.52  3973.4 1860.94  4022.8 1851.26  4058.4 1846.21  4072.6 1843.56
  4100.9 1836.44  4107.7 1833.84  4121.9 1831.61  4157.1 1827.28  4192.7 1824.31
  4298.7 1821.20  4581.8 1818.28  4744.7 1814.75  4815.0 1815.72  4829.2 1817.07
  4871.7 1815.85  4907.3 1812.46  4942.5 1812.31  4949.8 1810.94  4992.3 1811.47
  4999.2 1810.98  5002.9 1809.25  5003.4 1808.75  5023.7 1809.25  5034.6 1812.11
  5062.9 1816.43  5232.6 1814.01  5374.0 1818.79  5713.4 1824.47  6151.8 1838.17
#Mann=3,-1,0
  3923.8    0.05       0  5002.9    0.05       0  5023.7    0.05       0
Bank Sta=5002.9,5023.7
Exp/Cntr=0.3,0.1

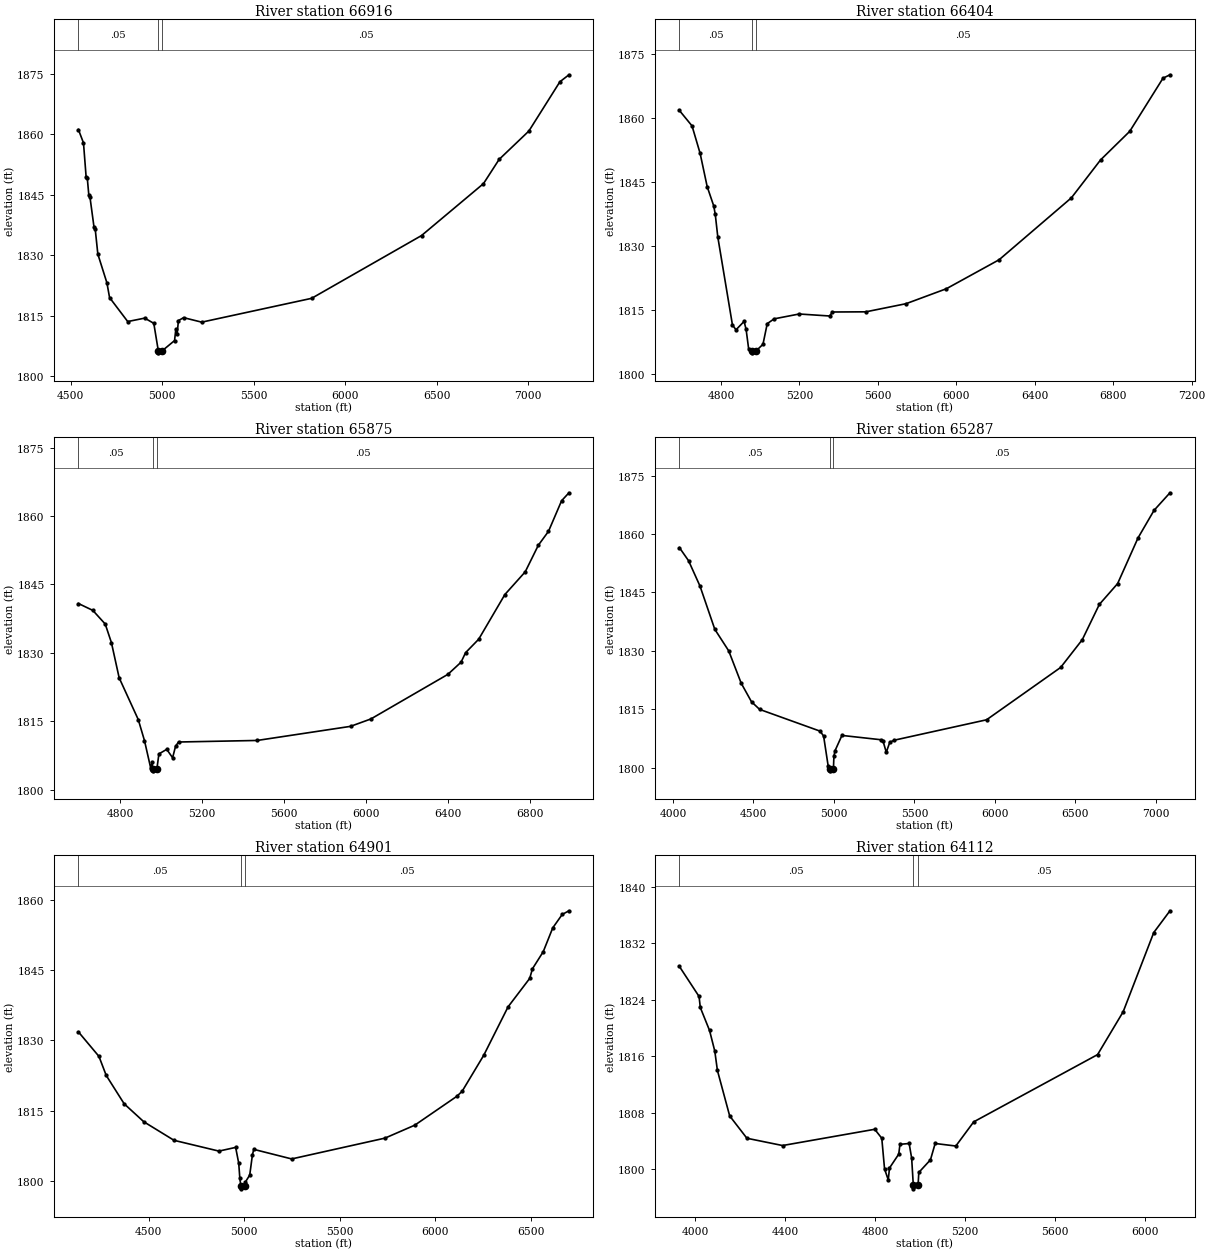
Type RM Length L Ch R = 1,66916,512,512,512
BEGIN DESCRIPTION:
Spring Creek 105.0
END DESCRIPTION:
XS GIS Cut Line= 3
      1652497.38      6887706.24      1652856.58      6887991.67
      1654455.02      6889538.02
#Sta/Elev= 30
  4541.2 1861.21  4569.1 1857.90  4583.5 1849.46  4589.9 1849.16  4598.0 1845.09
  4604.3 1844.54  4626.8 1836.95  4633.2 1836.53  4647.6 1830.31  4697.3 1823.17
  4711.7 1819.53  4811.0 1813.58  4903.9 1814.43  4953.6 1813.14  4978.3 1806.32
  4978.8 1805.82  4999.3 1806.32  5067.1 1808.86  5074.1 1811.69  5081.3 1810.48
  5088.2 1813.81  5116.5 1814.55  5215.6 1813.43  5816.7 1819.34  6417.7 1834.91
  6756.5 1847.79  6842.1 1853.80  7004.7 1860.83  7174.5 1873.06  7224.0 1874.79
#Mann=3,-1,0
  4541.2    0.05       0  4978.3    0.05       0  4999.3    0.05       0
Bank Sta=4978.3,4999.3
Exp/Cntr=0.3,0.1

Type RM Length L Ch R = 1,66404,529,529,529
BEGIN DESCRIPTION:
Spring Creek 104.0
END DESCRIPTION:
XS GIS Cut Line= 3
      1652405.01      6887938.03      1652505.00      6888338.00
      1654054.97      6889737.97
#Sta/Elev= 30
  4588.2 1861.80  4652.6 1858.18  4693.8 1851.74  4729.9 1843.91  4763.4 1839.37
  4771.1 1837.39  4784.0 1832.09  4858.7 1811.43  4876.8 1810.30  4918.0 1812.27
  4928.3 1810.39  4941.2 1805.85  4959.1 1805.39  4959.6 1804.89  4980.1 1805.39
  5014.3 1806.90  5036.0 1811.74  5071.1 1812.87  5198.9 1814.01  5354.3 1813.54
  5368.5 1814.48  5538.9 1814.52  5743.7 1816.43  5949.2 1819.94  6218.2 1826.75
  6586.6 1841.29  6735.3 1850.19  6884.0 1856.90  7053.6 1869.38  7089.1 1870.18
#Mann=3,-1,0
  4588.2    0.05       0  4959.1    0.03       0  4980.1    0.05       0
Bank Sta=4959.1,4980.1
Exp/Cntr=0.3,0.1

Type RM Length L Ch R = 1,65875,588,588,588
BEGIN DESCRIPTION:
Spring Creek 103.0
END DESCRIPTION:
XS GIS Cut Line= 3
      1652105.00      6888138.01      1652055.00      6888538.00
      1653304.98      6890087.97
#Sta/Elev= 30
  4595.9 1840.82  4666.4 1839.31  4726.9 1836.32  4757.1 1832.25  4794.9 1824.53
  4888.1 1815.38  4918.4 1810.78  4948.6 1804.81  4956.2 1806.00  4958.3 1804.64
  4958.8 1804.14  4979.3 1804.64  4988.9 1807.85  5027.0 1808.85  5055.8 1807.01
  5070.2 1809.53  5084.6 1810.46  5468.4 1810.80  5924.0 1813.89  6023.4 1815.51
  6399.3 1825.29  6463.5 1827.95  6485.6 1830.04  6549.6 1832.99  6677.5 1842.79
  6776.7 1847.76  6840.7 1853.59  6890.3 1856.64  6954.3 1863.35  6990.2 1865.09
#Mann=3,-1,0
  4595.9    0.05       0  4958.3    0.03       0  4979.3    0.05       0
Bank Sta=4958.3,4979.3
Exp/Cntr=0.3,0.1

Type RM Length L Ch R = 1,65287,386,386,386
BEGIN DESCRIPTION:
Spring Creek 102.0
END DESCRIPTION:
XS GIS Cut Line= 3
      1651005.00      6888138.00      1651605.00      6888888.00
      1653154.98      6890287.98
#Sta/Elev= 30
  4039.5 1856.50  4096.3 1853.15  4167.6 1846.62  4259.6 1835.53  4346.1 1830.00
  4423.7 1821.69  4487.7 1816.93  4538.1 1814.98  4914.3 1809.39  4935.9 1808.13
  4964.0 1800.50  4975.9 1799.71  4976.4 1799.21  4996.9 1799.71  5000.0 1803.02
  5007.1 1804.40  5049.7 1808.30  5290.3 1807.20  5304.5 1806.94  5325.4 1803.97
  5347.1 1806.54  5375.5 1807.08  5948.7 1812.31  6409.0 1825.74  6543.5 1832.86
  6649.6 1841.92  6763.2 1847.26  6890.2 1859.00  6989.6 1866.06  7088.6 1870.57
#Mann=3,-1,0
  4039.5    0.05       0  4975.9    0.03       0  4996.9    0.05       0
Bank Sta=4975.9,4996.9
Exp/Cntr=0.3,0.1

Type RM Length L Ch R = 1,64901,789,789,789
BEGIN DESCRIPTION:
Spring Creek 101.0
END DESCRIPTION:
XS GIS Cut Line= 3
      1650959.16      6888407.61      1651375.83      6889174.98
      1652555.00      6890388.00
#Sta/Elev= 30
  4133.1 1831.79  4240.6 1826.56  4278.7 1822.49  4372.5 1816.44  4475.4 1812.60
  4633.2 1808.65  4867.9 1806.35  4955.3 1807.14  4971.5 1803.75  4977.2 1800.51
  4982.9 1798.80  4983.4 1798.30  5003.9 1798.80  5005.2 1799.68  5029.0 1801.24
  5043.2 1805.61  5050.3 1806.72  5248.2 1804.68  5736.1 1809.12  5891.8 1811.88
  6111.1 1818.02  6139.4 1819.11  6252.4 1826.79  6379.7 1837.13  6492.9 1843.20
  6507.0 1845.24  6563.6 1848.90  6613.2 1853.97  6662.6 1856.83  6698.0 1857.62
#Mann=3,-1,0
  4133.1    0.05       0  4982.9    0.03       0  5003.9    0.05       0
Bank Sta=4982.9,5003.9
Exp/Cntr=0.3,0.1

Type RM Length L Ch R = 1,64112,429,429,429
BEGIN DESCRIPTION:
Spring Creek 100.0
END DESCRIPTION:
XS GIS Cut Line= 3
      1650824.44      6888703.35      1651256.85      6889681.76
      1652154.96      6890337.97
#Sta/Elev= 30
  3930.3 1828.69  4017.8 1824.44  4023.3 1822.88  4064.4 1819.63  4087.7 1816.71
  4099.4 1813.97  4154.0 1807.53  4230.6 1804.37  4389.2 1803.34  4799.1 1805.64
  4830.5 1804.37  4842.8 1800.02  4859.3 1798.48  4864.8 1800.16  4905.9 1802.12
  4911.4 1803.51  4952.2 1803.63  4963.4 1801.55  4970.7 1797.71  4971.2 1797.21
  4991.9 1797.71  4995.2 1799.53  5047.0 1801.32  5067.9 1803.63  5159.8 1803.27
  5239.3 1806.69  5790.3 1816.21  5904.2 1822.28  6040.2 1833.49  6112.3 1836.57
#Mann=3,-1,0
  3930.3    0.05       0  4970.7    0.03       0  4991.9    0.05       0
Bank Sta=4970.7,4991.9
Exp/Cntr=0.3,0.1

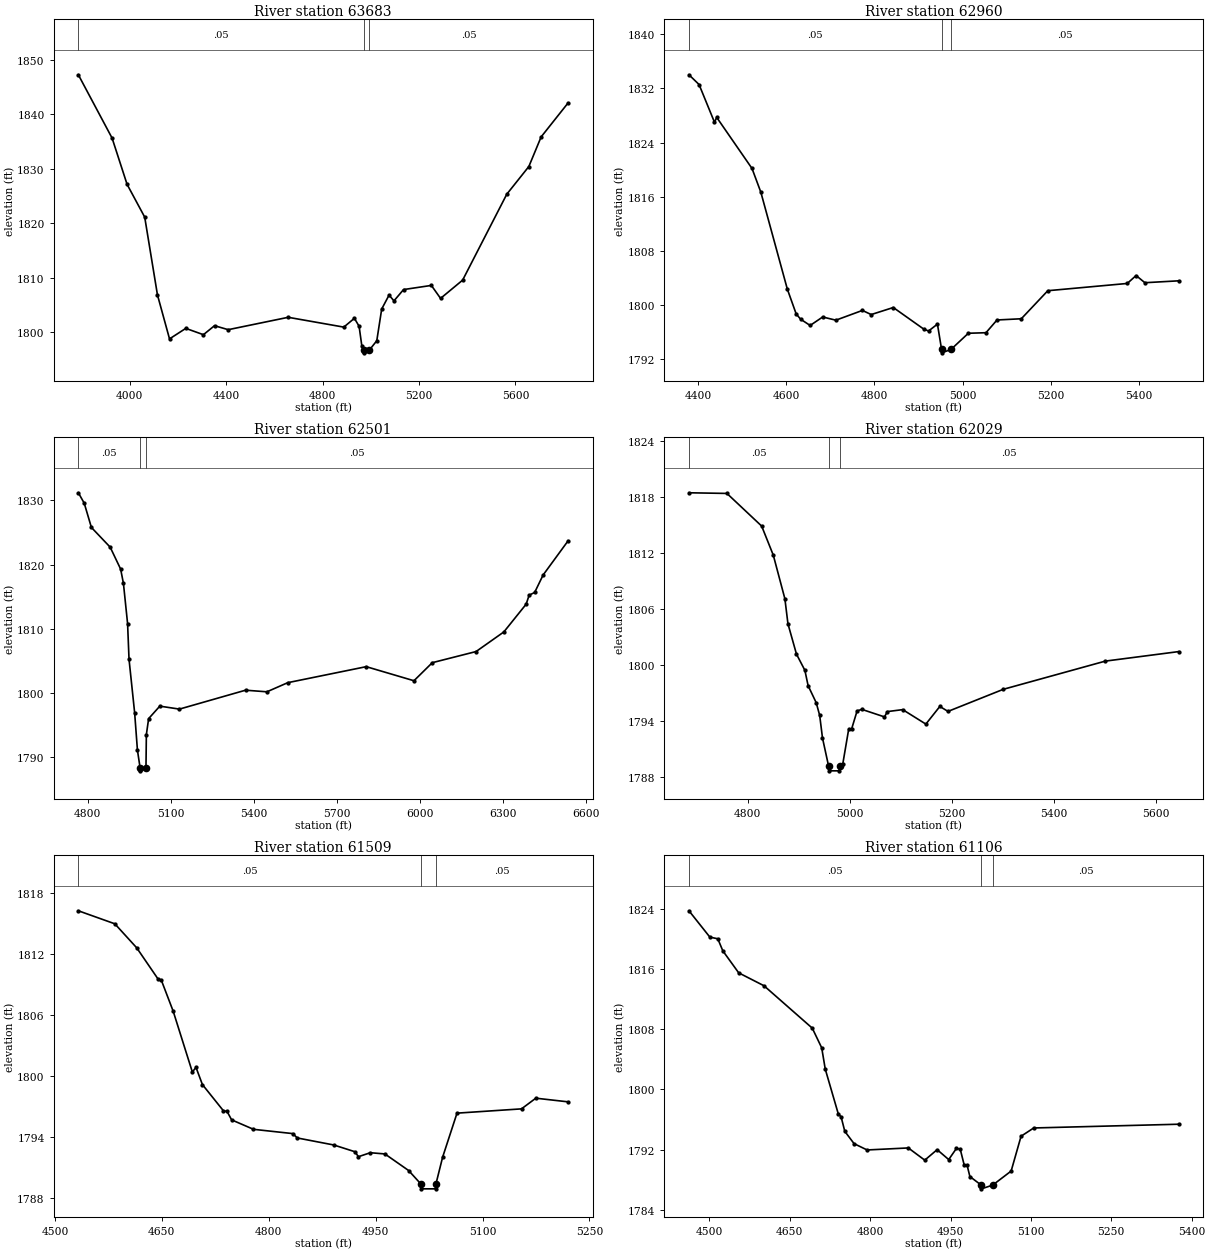
Type RM Length L Ch R = 1,63683,723,723,723
BEGIN DESCRIPTION:
Spring Creek 99.0
END DESCRIPTION:
XS GIS Cut Line= 3
      1650555.00      6888787.99      1650955.00      6889938.00
      1651104.99      6890737.97
#Sta/Elev= 30
  3786.7 1847.20  3926.7 1835.58  3988.9 1827.09  4062.0 1821.08  4114.9 1806.80
  4164.9 1798.74  4232.4 1800.67  4305.5 1799.51  4351.5 1801.16  4408.4 1800.43
  4657.2 1802.70  4887.8 1800.90  4931.8 1802.52  4951.3 1801.05  4962.9 1797.35
  4972.5 1796.68  4973.0 1796.18  4993.7 1796.68  5024.6 1798.40  5045.0 1804.22
  5075.5 1806.77  5095.9 1805.72  5135.7 1807.79  5251.0 1808.55  5289.2 1806.17
  5380.7 1809.52  5563.9 1825.29  5655.4 1830.37  5706.3 1835.80  5818.2 1842.04
#Mann=3,-1,0
  3786.7    0.05       0  4972.5    0.03       0  4993.7    0.05       0
Bank Sta=4972.5,4993.7
Exp/Cntr=0.3,0.1

Type RM Length L Ch R = 1,62960,459,459,459
BEGIN DESCRIPTION:
Mapping XS 27f436e4
END DESCRIPTION:
XS GIS Cut Line= 2
      1650572.71      6888955.14      1650520.71      6890064.62
#Sta/Elev= 30
  4379.5 1834.02  4402.4 1832.58  4437.4 1827.01  4442.4 1827.73  4522.5 1820.19
  4542.5 1816.69  4602.6 1802.38  4622.6 1798.73  4632.6 1797.95  4654.3 1797.02
  4682.7 1798.27  4712.7 1797.80  4772.8 1799.24  4792.8 1798.63  4842.9 1799.67
  4912.9 1796.44  4923.0 1796.21  4943.0 1797.22  4952.4 1793.48  4952.9 1792.98
  4973.7 1793.48  5013.1 1795.87  5053.1 1795.95  5078.1 1797.83  5133.2 1798.01
  5193.3 1802.15  5373.5 1803.22  5393.5 1804.39  5413.5 1803.33  5490.2 1803.61
#Mann=3,-1,0
  4379.5    0.05       0  4952.4    0.03       0  4973.7    0.05       0
Bank Sta=4952.4,4973.7
Exp/Cntr=0.3,0.1

Type RM Length L Ch R = 1,62501,472,472,472
BEGIN DESCRIPTION:
Mapping XS e8474281
END DESCRIPTION:
XS GIS Cut Line= 3
      1650212.64      6889056.96      1650278.61      6889480.53
      1650740.20      6890740.36
#Sta/Elev= 30
  4766.3 1831.16  4787.6 1829.54  4813.5 1825.77  4881.4 1822.70  4919.2 1819.29
  4929.3 1817.07  4944.3 1810.82  4949.5 1805.28  4969.8 1796.96  4979.9 1791.14
  4989.4 1788.42  4989.9 1787.92  5010.8 1788.42  5012.2 1793.56  5020.4 1796.04
  5060.8 1797.98  5131.7 1797.52  5370.7 1800.46  5447.9 1800.21  5523.3 1801.63
  5807.0 1804.12  5979.5 1801.93  6045.8 1804.74  6204.0 1806.47  6304.4 1809.52
  6385.1 1813.84  6395.9 1815.24  6415.8 1815.66  6446.3 1818.37  6536.7 1823.69
#Mann=3,-1,0
  4766.3    0.05       0  4989.4    0.05       0  5010.8    0.05       0
Bank Sta=4989.4,5010.8
Exp/Cntr=0.3,0.1

Type RM Length L Ch R = 1,62029,520,520,520
BEGIN DESCRIPTION:
Spring Creek 98.0
END DESCRIPTION:
XS GIS Cut Line= 3
      1649719.58      6889202.74      1649855.00      6889488.00
      1650169.14      6890050.33
#Sta/Elev= 30
  4684.6 1818.47  4759.0 1818.40  4827.1 1814.90  4849.9 1811.78  4872.6 1807.11
  4878.6 1804.43  4895.3 1801.18  4911.8 1799.44  4918.1 1797.80  4934.0 1795.97
  4940.8 1794.61  4946.3 1792.19  4958.3 1789.17  4958.8 1788.67  4979.2 1788.67
  4979.7 1789.17  4986.2 1789.45  4997.6 1793.12  5003.2 1793.12  5014.1 1795.09
  5023.3 1795.26  5067.8 1794.45  5073.5 1795.02  5103.5 1795.23  5148.9 1793.68
  5176.3 1795.57  5192.3 1795.04  5300.8 1797.41  5500.7 1800.43  5644.5 1801.45
#Mann=3,-1,0
  4684.6    0.05       0  4958.3    0.03       0  4979.7    0.05       0
Bank Sta=4958.3,4979.7
Exp/Cntr=0.3,0.1

Type RM Length L Ch R = 1,61509,403,403,403
BEGIN DESCRIPTION:
Spring Creek 97.0
END DESCRIPTION:
XS GIS Cut Line= 3
      1649654.99      6889288.04      1649555.00      6889738.00
      1649580.00      6889962.98
#Sta/Elev= 30
  4532.8 1816.24  4584.0 1814.96  4614.7 1812.60  4644.2 1809.58  4649.3 1809.41
  4665.9 1806.37  4692.8 1800.39  4697.9 1800.85  4706.9 1799.16  4736.4 1796.58
  4741.5 1796.52  4747.9 1795.69  4778.6 1794.76  4833.7 1794.34  4840.1 1793.91
  4891.3 1793.22  4920.8 1792.56  4925.9 1792.07  4942.5 1792.46  4963.0 1792.34
  4996.3 1790.71  5013.2 1789.41  5013.7 1788.91  5034.2 1788.91  5034.7 1789.41
  5044.0 1792.02  5064.2 1796.35  5154.7 1796.77  5174.8 1797.82  5220.1 1797.46
#Mann=3,-1,0
  4532.8    0.05       0  5013.2    0.03       0  5034.7    0.05       0
Bank Sta=5013.2,5034.7
Exp/Cntr=0.3,0.1

Type RM Length L Ch R = 1,61106,326,326,326
BEGIN DESCRIPTION:
Spring Creek 96.0
END DESCRIPTION:
XS GIS Cut Line= 3
      1648955.02      6889238.05      1649146.67      6889716.65
      1649270.86      6890095.15
#Sta/Elev= 30
  4461.9 1823.81  4500.9 1820.30  4515.7 1820.08  4525.1 1818.47  4554.7 1815.54
  4601.9 1813.82  4692.0 1808.17  4709.6 1805.55  4716.2 1802.72  4740.4 1796.78
  4745.8 1796.35  4752.7 1794.42  4770.0 1792.78  4794.3 1791.94  4871.2 1792.21
  4901.9 1790.58  4925.0 1791.98  4946.6 1790.66  4961.1 1792.16  4968.1 1792.04
  4975.5 1789.93  4980.8 1789.93  4986.1 1788.40  5007.2 1787.26  5007.7 1786.76
  5028.7 1787.26  5063.1 1789.13  5081.6 1793.77  5105.2 1794.87  5375.8 1795.37
#Mann=3,-1,0
  4461.9    0.05       0  5007.2    0.03       0  5028.7    0.05       0
Bank Sta=5007.2,5028.7
Exp/Cntr=0.3,0.1

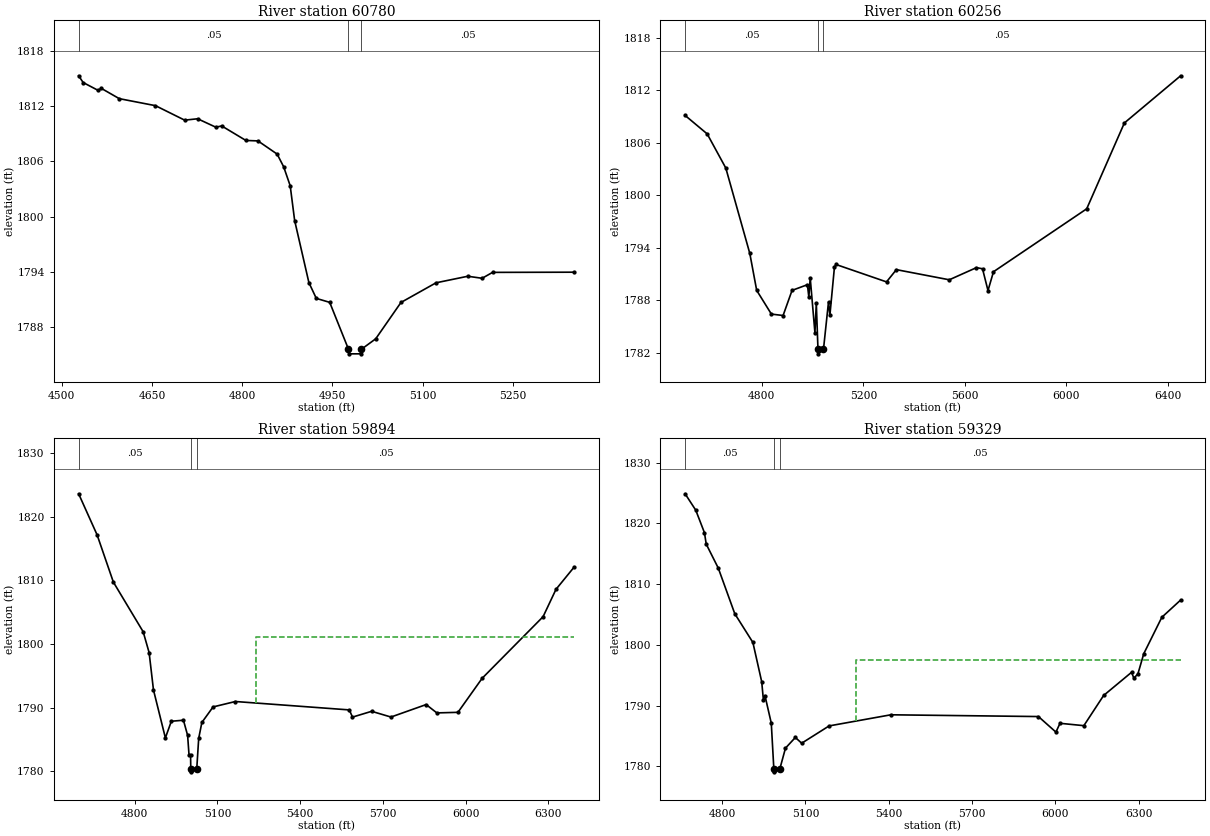
Type RM Length L Ch R = 1,60780,524,524,524
BEGIN DESCRIPTION:
Mapping XS f25e8c7a
END DESCRIPTION:
XS GIS Cut Line= 3
      1648757.78      6889230.53      1648778.61      6889536.09
      1648980.02      6890013.04
#Sta/Elev= 30
  4528.2 1815.26  4535.7 1814.53  4560.8 1813.67  4565.8 1813.90  4595.8 1812.78
  4656.0 1812.02  4704.5 1810.45  4726.1 1810.60  4756.2 1809.69  4766.2 1809.82
  4806.3 1808.25  4826.4 1808.20  4858.3 1806.77  4869.1 1805.40  4880.0 1803.34
  4887.4 1799.57  4911.1 1792.84  4923.4 1791.13  4945.7 1790.70  4976.9 1785.62
  4977.4 1785.12  4998.0 1785.12  4998.5 1785.62  5022.2 1786.75  5064.2 1790.69
  5122.5 1792.82  5175.3 1793.53  5199.1 1793.31  5216.5 1793.95  5352.2 1793.97
#Mann=3,-1,0
  4528.2    0.05       0  4976.9    0.03       0  4998.5    0.05       0
Bank Sta=4976.9,4998.5
Exp/Cntr=0.3,0.1

Type RM Length L Ch R = 1,60256,362,362,362
BEGIN DESCRIPTION:
Spring Creek 95.0
END DESCRIPTION:
XS GIS Cut Line= 3
      1648323.77      6889459.73      1648577.22      6889869.42
      1649132.79      6891230.55
#Sta/Elev= 30
  4497.8 1809.11  4584.8 1807.00  4658.1 1803.10  4752.7 1793.34  4779.8 1789.12
  4837.7 1786.41  4883.8 1786.25  4919.1 1789.12  4979.6 1789.77  4985.2 1788.35
  4990.6 1790.56  5009.2 1784.27  5014.6 1787.66  5021.2 1782.37  5021.7 1781.87
  5042.8 1782.37  5062.7 1787.81  5068.1 1786.27  5086.0 1791.76  5092.1 1792.08
  5291.2 1790.09  5330.0 1791.49  5538.4 1790.33  5645.4 1791.72  5669.3 1791.59
  5690.9 1789.10  5712.5 1791.25  6079.7 1798.44  6228.1 1808.25  6449.7 1813.64
#Mann=3,-1,0
  4497.8    0.05       0  5021.2    0.03       0  5042.8    0.05       0
Bank Sta=5021.2,5042.8
Exp/Cntr=0.3,0.1

Type RM Length L Ch R = 1,59894,565,565,565
BEGIN DESCRIPTION:
Spring Creek 94.0
END DESCRIPTION:
XS GIS Cut Line= 3
      1648054.98      6889537.97      1648255.00      6889888.00
      1648816.46      6891163.77
#Sta/Elev= 30
  4596.7 1823.59  4663.7 1817.13  4722.7 1809.71  4830.7 1801.91  4852.3 1798.64
  4868.1 1792.77  4911.3 1785.23  4932.9 1787.85  4976.8 1788.01  4991.9 1785.63
  4997.0 1782.57  5002.6 1782.57  5003.4 1780.40  5003.9 1779.90  5025.1 1780.40
  5032.1 1785.16  5043.6 1787.66  5084.3 1790.10  5165.2 1790.95  5578.3 1789.63
  5589.8 1788.50  5659.3 1789.41  5729.3 1788.51  5856.9 1790.47  5895.7 1789.16
  5972.2 1789.25  6060.0 1794.60  6281.0 1804.28  6327.7 1808.57  6393.7 1812.08
#Mann=3,-1,0
  4596.7    0.05       0  5003.4    0.05       0  5025.1    0.05       0
#XS Ineff=2,0
       0                 5241.10    0.00 1801.09
Permanent Ineff=
       F       F
Bank Sta=5003.4,5025.1
Exp/Cntr=0.3,0.1

Type RM Length L Ch R = 1,59329,292,292,292
BEGIN DESCRIPTION:
Spring Creek 93.0
END DESCRIPTION:
XS GIS Cut Line= 3
      1647542.51      6889647.22      1647705.00      6889938.00
      1648556.38      6891112.47
#Sta/Elev= 30
  4666.8 1824.89  4705.2 1822.19  4736.4 1818.49  4742.9 1816.60  4786.3 1812.65
  4845.7 1805.14  4910.8 1800.42  4942.6 1793.94  4948.5 1791.02  4954.2 1791.68
  4977.0 1787.14  4986.2 1779.62  4986.7 1779.12  5007.9 1779.62  5028.1 1783.02
  5063.7 1784.78  5086.4 1783.83  5185.2 1786.68  5407.5 1788.51  5938.6 1788.22
  6001.6 1785.66  6016.3 1787.11  6102.1 1786.72  6173.3 1791.69  6273.7 1795.50
  6282.3 1794.53  6296.8 1795.26  6317.8 1798.57  6382.8 1804.56  6450.5 1807.40
#Mann=3,-1,0
  4666.8    0.05       0  4986.2    0.05       0  5007.9    0.05       0
#XS Ineff=2,0
       0                 5281.90    0.00 1797.55
Permanent Ineff=
       F       F
Bank Sta=4986.2,5007.9
Exp/Cntr=0.3,0.1