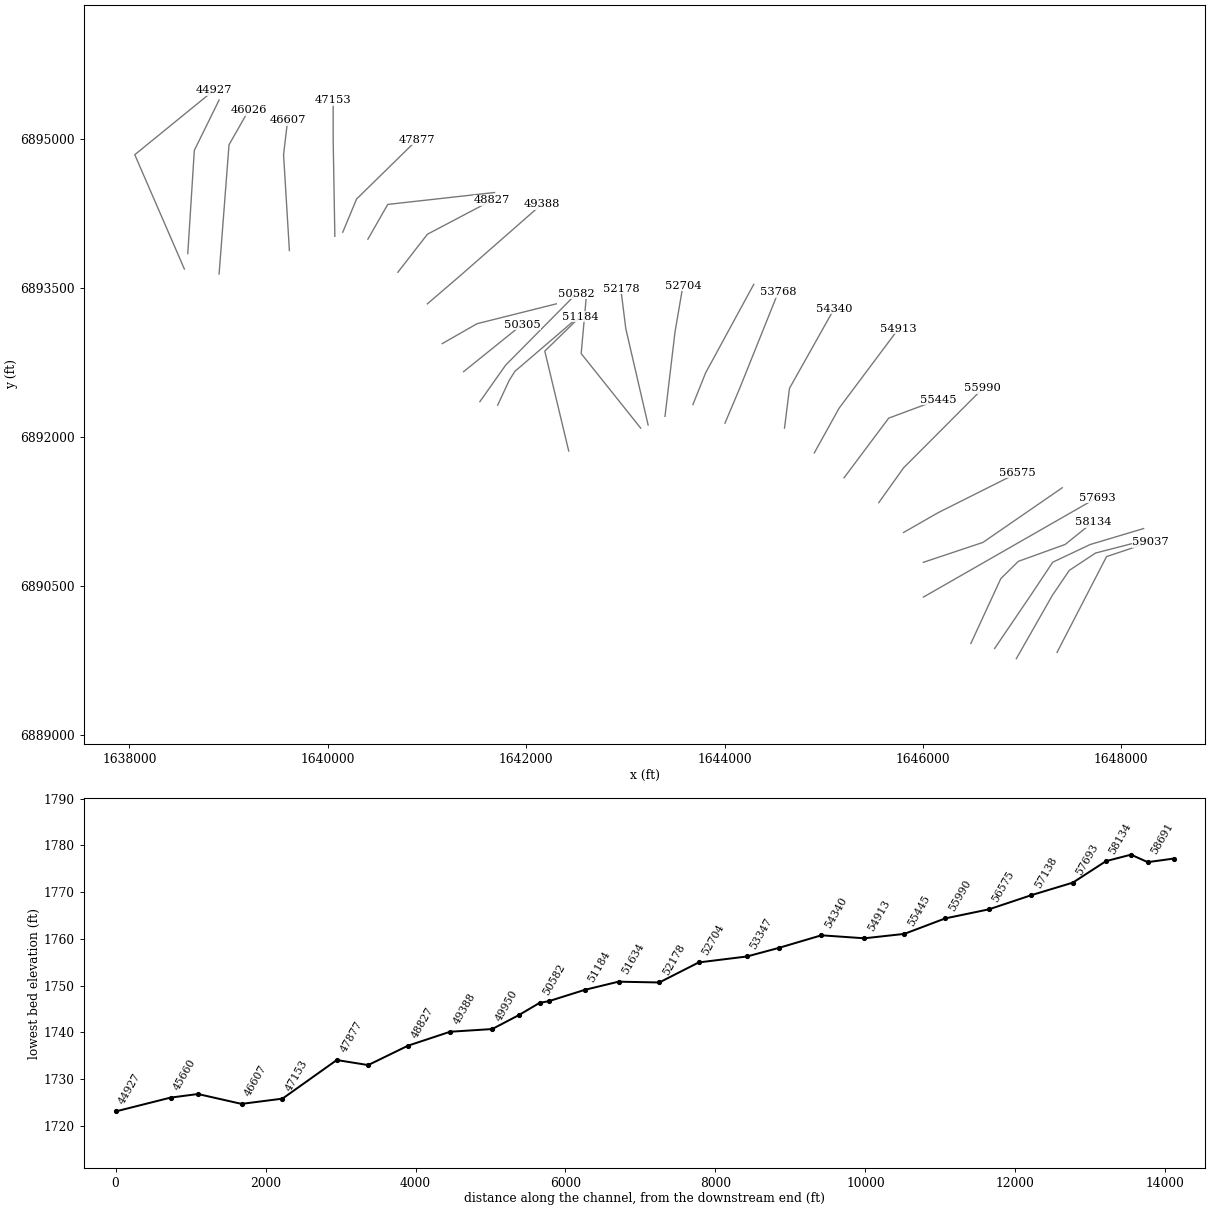
HEC-RAS study Spring Creek.prj: Spring Creek Base Level Engineering

--- Spring Creek.g01 (geometry) --- (continued)

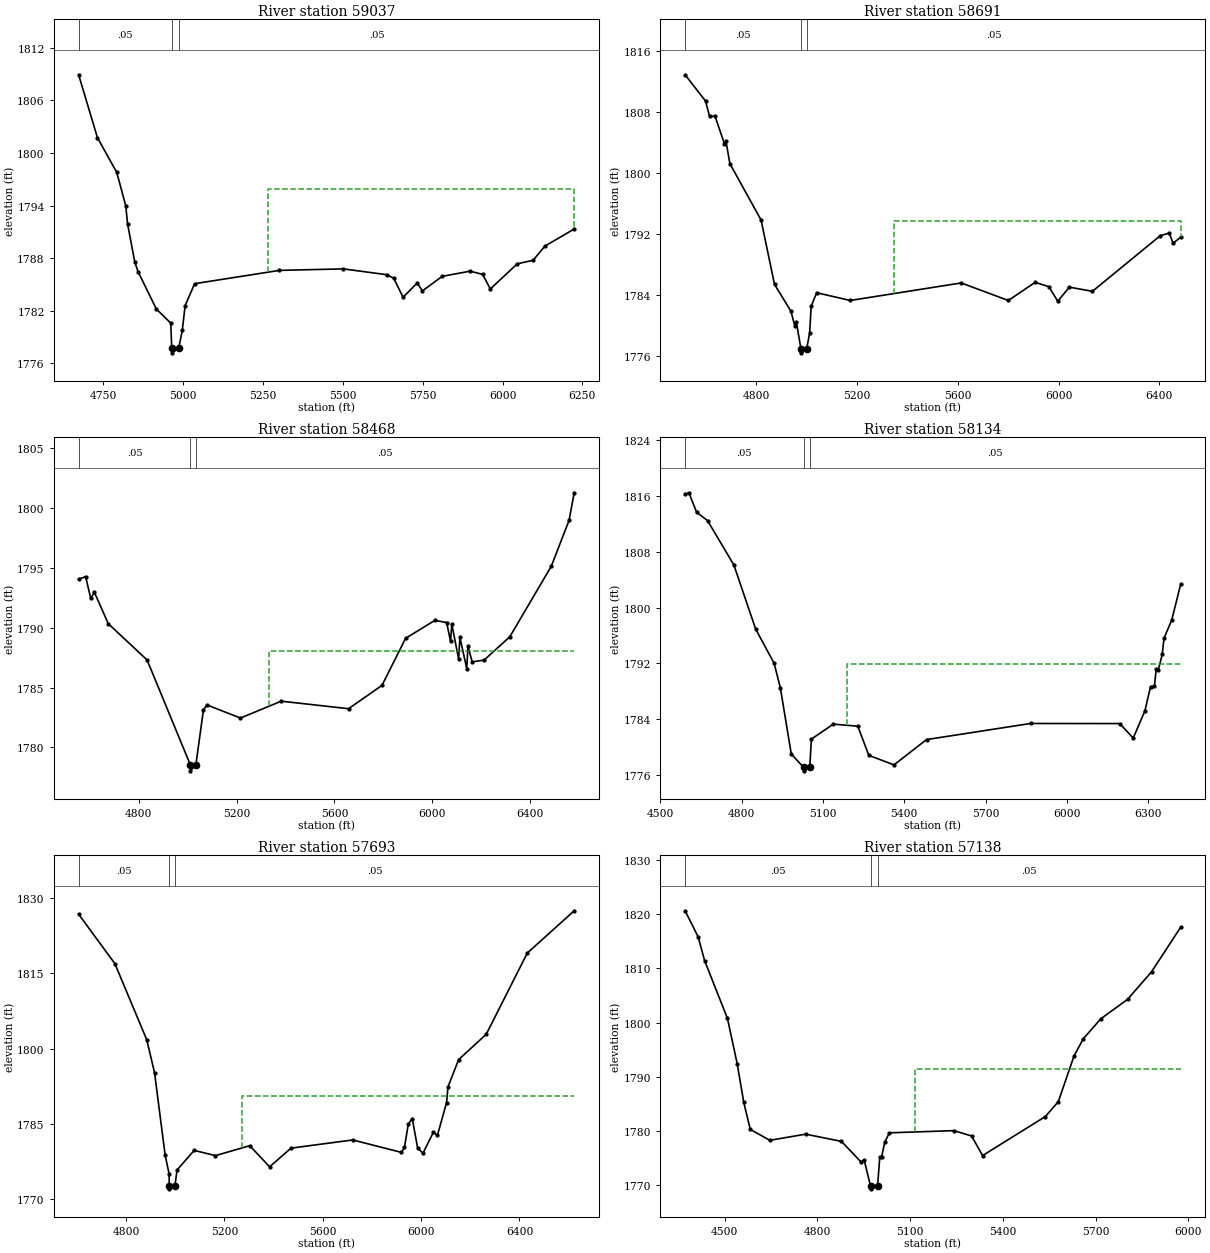
Type RM Length L Ch R = 1,59037,346,346,346
BEGIN DESCRIPTION:
Mapping XS a61110c5
END DESCRIPTION:
XS GIS Cut Line= 4
      1647352.23      6889831.86      1647664.73      6890435.15
      1647851.36      6890795.39      1648294.07      6890942.97
#Sta/Elev= 30
  4672.5 1808.93  4731.5 1801.74  4792.0 1797.78  4820.0 1793.99  4825.8 1791.91
  4848.3 1787.57  4858.6 1786.46  4915.9 1782.20  4961.0 1780.59  4964.1 1777.70
  4964.6 1777.20  4985.8 1777.70  4997.1 1779.78  5006.0 1782.59  5035.7 1785.09
  5301.3 1786.61  5501.5 1786.78  5636.7 1786.12  5659.2 1785.72  5688.4 1783.54
  5732.7 1785.17  5749.2 1784.27  5811.1 1785.93  5898.5 1786.52  5937.6 1786.15
  5961.8 1784.49  6046.1 1787.36  6095.7 1787.76  6132.6 1789.38  6224.3 1791.33
#Mann=3,-1,0
  4672.5    0.05       0  4964.1    0.05       0  4985.8    0.05       0
#XS Ineff=2,0
    0.00 4735.40 1795.91 5264.60    0.00 1795.91
Permanent Ineff=
       F       F
Bank Sta=4964.1,4985.8
Exp/Cntr=0.3,0.1

Type RM Length L Ch R = 1,58691,223,223,223
BEGIN DESCRIPTION:
Spring Creek 92.0
END DESCRIPTION:
XS GIS Cut Line= 5
      1646941.80      6889768.72      1647306.39      6890407.62
      1647475.84      6890656.83      1647740.42      6890831.23
      1648334.13      6890984.00
#Sta/Elev= 30
  4517.3 1812.92  4598.6 1809.47  4614.4 1807.45  4636.0 1807.50  4673.5 1803.86
  4679.2 1804.27  4695.1 1801.26  4818.9 1793.86  4872.2 1785.42  4937.0 1781.92
  4952.9 1779.98  4958.6 1780.54  4977.2 1776.94  4977.7 1776.44  4999.8 1776.94
  5011.6 1779.04  5017.7 1782.53  5039.3 1784.33  5172.7 1783.31  5613.1 1785.61
  5800.2 1783.31  5906.9 1785.69  5961.1 1785.12  5996.6 1783.21  6042.5 1785.06
  6134.0 1784.51  6403.8 1791.82  6439.4 1792.15  6454.1 1790.81  6484.2 1791.60
#Mann=3,-1,0
  4517.3    0.05       0  4977.2    0.05       0  4999.8    0.05       0
#XS Ineff=2,0
       0                 5344.80    0.00 1793.72
Permanent Ineff=
       F       F
Bank Sta=4977.2,4999.8
Exp/Cntr=0.3,0.1

Type RM Length L Ch R = 1,58468,334,334,334
BEGIN DESCRIPTION:
Mapping XS 64373c42
END DESCRIPTION:
XS GIS Cut Line= 5
      1646722.90      6889870.93      1647091.81      6890413.45
      1647308.83      6890738.97      1647686.43      6890916.92
      1648224.65      6891077.52
#Sta/Elev= 30
  4553.8 1794.05  4582.4 1794.27  4603.3 1792.44  4618.3 1792.95  4675.2 1790.33
  4833.8 1787.30  5010.6 1778.54  5011.1 1778.04  5033.2 1778.54  5064.3 1783.15
  5079.2 1783.54  5215.6 1782.45  5382.2 1783.86  5657.6 1783.23  5794.3 1785.18
  5890.9 1789.11  6010.4 1790.61  6058.8 1790.43  6074.6 1788.85  6079.8 1790.29
  6107.7 1787.39  6113.0 1789.18  6140.9 1786.58  6146.1 1788.46  6163.1 1787.14
  6212.4 1787.30  6317.0 1789.24  6486.6 1795.13  6559.4 1798.97  6580.2 1801.27
#Mann=3,-1,0
  4553.8    0.05       0  5010.6    0.05       0  5033.2    0.05       0
#XS Ineff=2,0
    0.00 4667.10 1788.09 5332.90    0.00 1788.09
Permanent Ineff=
       F       F
Bank Sta=5010.6,5033.2
Exp/Cntr=0.3,0.1

Type RM Length L Ch R = 1,58134,441,441,441
BEGIN DESCRIPTION:
Spring Creek 91.0
END DESCRIPTION:
XS GIS Cut Line= 5
      1646483.47      6889921.51      1646785.56      6890574.28
      1646962.64      6890747.90      1647434.86      6890918.03
      1647715.62      6891143.34
#Sta/Elev= 30
  4590.9 1816.19  4605.0 1816.41  4633.4 1813.63  4673.8 1812.43  4771.0 1806.08
  4851.5 1796.91  4919.5 1792.03  4942.5 1788.52  4982.8 1779.06  5028.3 1777.15
  5028.8 1776.65  5051.0 1777.15  5057.1 1781.19  5138.0 1783.33  5228.6 1783.03
  5268.9 1778.87  5362.0 1777.50  5482.1 1781.12  5865.9 1783.42  6195.4 1783.41
  6245.0 1781.33  6288.2 1785.23  6309.0 1788.68  6323.4 1788.72  6329.8 1791.21
  6337.8 1791.09  6352.2 1793.30  6358.6 1795.59  6387.4 1798.24  6420.1 1803.31
#Mann=3,-1,0
  4590.9    0.05       0  5028.3    0.05       0  5051.0    0.05       0
#XS Ineff=2,0
    0.00 4810.70 1791.92 5189.30    0.00 1791.92
Permanent Ineff=
       F       F
Bank Sta=5028.3,5051
Exp/Cntr=0.3,0.1

Type RM Length L Ch R = 1,57693,555,555,555
BEGIN DESCRIPTION:
Spring Creek 90.0
END DESCRIPTION:
XS GIS Cut Line= 3
      1646005.02      6890388.01      1646355.00      6890588.00
      1647754.97      6891387.98
#Sta/Elev= 30
  4607.0 1826.79  4754.5 1816.93  4884.1 1801.76  4915.8 1795.19  4959.0 1778.73
  4974.8 1775.08  4975.7 1772.56  4976.2 1772.06  4998.4 1772.56  5007.2 1775.82
  5077.0 1779.72  5163.4 1778.68  5303.1 1780.66  5383.7 1776.45  5470.8 1780.17
  5722.0 1781.80  5920.0 1779.32  5932.2 1780.31  5948.0 1785.00  5963.9 1786.06
  5985.5 1780.27  6007.1 1779.13  6050.3 1783.37  6066.1 1782.70  6103.5 1789.23
  6109.3 1792.38  6152.5 1797.81  6264.8 1802.86  6431.8 1819.04  6622.5 1827.47
#Mann=3,-1,0
  4607.0    0.05       0  4975.7    0.05       0  4998.4    0.05       0
#XS Ineff=2,0
       0                 5270.70    0.00 1790.64
Permanent Ineff=
       F       F
Bank Sta=4975.7,4998.4
Exp/Cntr=0.3,0.1

Type RM Length L Ch R = 1,57138,563,563,563
BEGIN DESCRIPTION:
Spring Creek 89.0
END DESCRIPTION:
XS GIS Cut Line= 3
      1646005.03      6890738.01      1646605.00      6890938.00
      1647404.96      6891487.97
#Sta/Elev= 30
  4372.1 1820.59  4414.2 1815.81  4435.3 1811.39  4509.1 1800.77  4540.7 1792.39
  4561.8 1785.32  4582.9 1780.32  4646.1 1778.31  4762.1 1779.44  4878.0 1778.11
  4941.3 1774.32  4951.8 1774.61  4972.1 1769.87  4972.6 1769.37  4994.8 1769.87
  5001.9 1775.19  5007.6 1775.19  5018.0 1777.94  5032.9 1779.69  5242.0 1780.09
  5298.8 1779.11  5334.7 1775.50  5537.7 1782.69  5579.6 1785.44  5630.3 1793.83
  5659.8 1796.97  5716.9 1800.69  5803.5 1804.27  5881.3 1809.36  5975.3 1817.55
#Mann=3,-1,0
  4372.1    0.05       0  4972.1    0.05       0  4994.8    0.05       0
#XS Ineff=2,0
       0                 5115.70    0.00 1791.53
Permanent Ineff=
       F       F
Bank Sta=4972.1,4994.8
Exp/Cntr=0.3,0.1

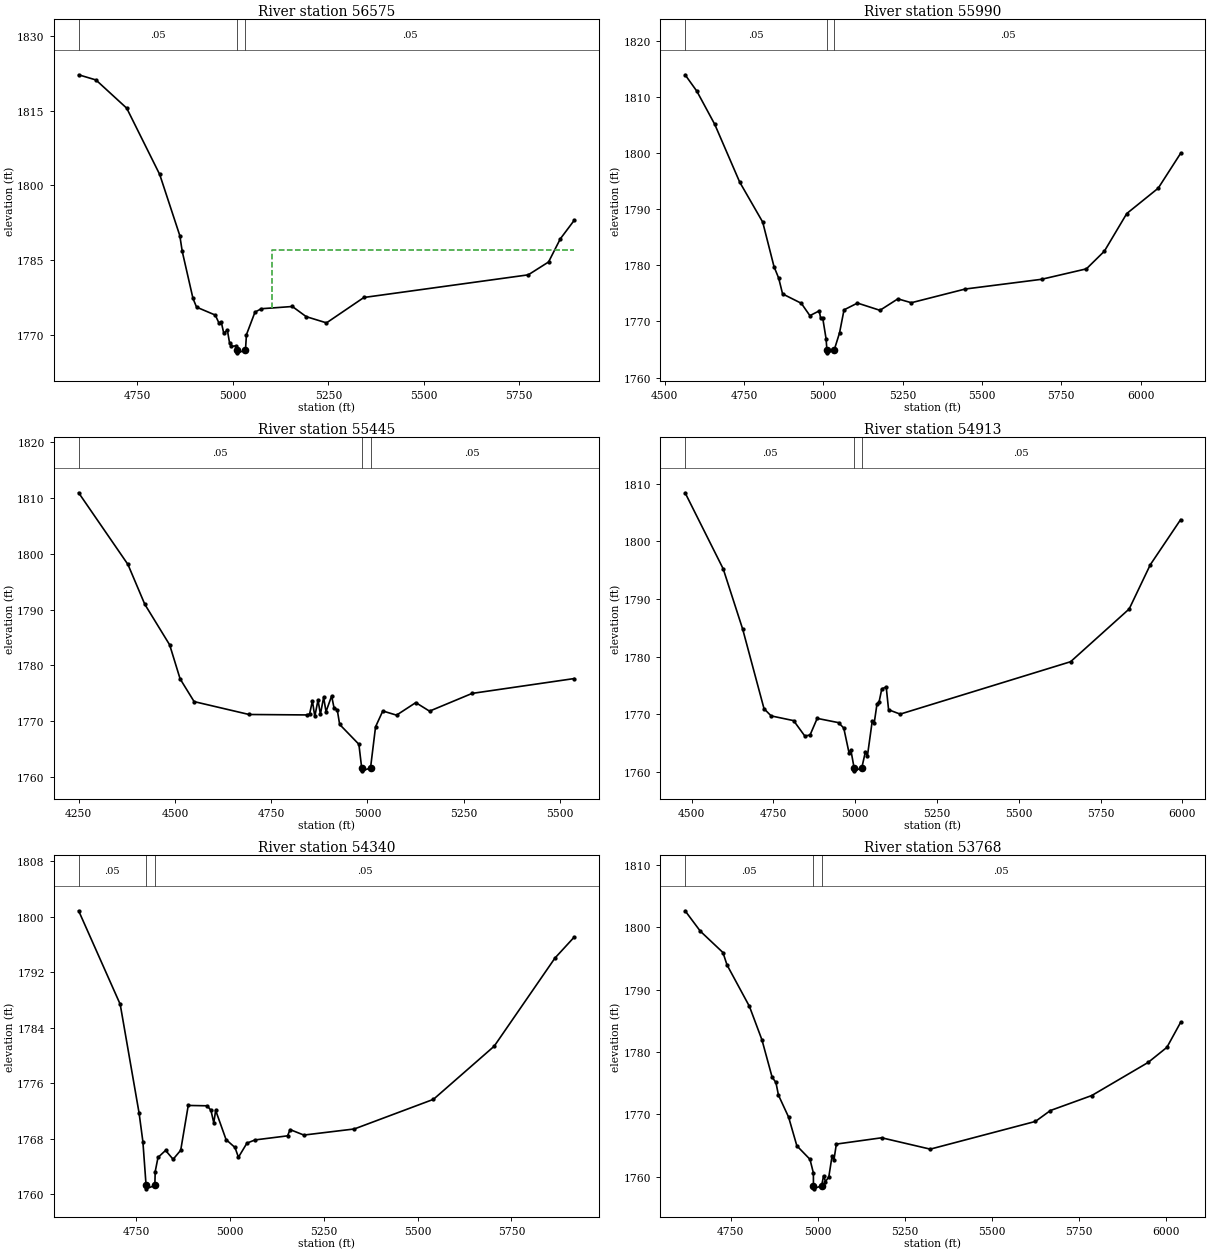
Type RM Length L Ch R = 1,56575,585,585,585
BEGIN DESCRIPTION:
Spring Creek 88.0
END DESCRIPTION:
XS GIS Cut Line= 3
      1645805.03      6891038.02      1646155.00      6891238.00
      1646954.99      6891638.00
#Sta/Elev= 30
  4596.1 1822.21  4641.4 1821.17  4722.0 1815.50  4808.4 1802.18  4861.0 1789.90
  4867.4 1786.72  4895.5 1777.28  4904.9 1775.53  4953.8 1773.94  4963.9 1772.28
  4969.7 1772.49  4976.1 1770.28  4985.5 1770.92  4991.3 1768.34  4996.3 1767.63
  5007.6 1767.76  5010.2 1766.85  5010.7 1766.35  5032.9 1766.85  5035.5 1770.00
  5057.9 1774.54  5074.6 1775.21  5155.7 1775.66  5192.0 1773.62  5245.1 1772.37
  5343.0 1777.47  5773.4 1782.02  5826.5 1784.60  5857.3 1789.25  5893.6 1792.96
#Mann=3,-1,0
  4596.1    0.05       0  5010.2    0.05       0  5032.9    0.05       0
#XS Ineff=2,0
       0                 5101.70    0.00 1786.97
Permanent Ineff=
       F       F
Bank Sta=5010.2,5032.9
Exp/Cntr=0.3,0.1

Type RM Length L Ch R = 1,55990,545,545,545
BEGIN DESCRIPTION:
Spring Creek 87.0
END DESCRIPTION:
XS GIS Cut Line= 3
      1645555.01      6891338.01      1645805.00      6891688.00
      1646605.02      6892488.02
#Sta/Elev= 30
  4564.6 1813.90  4601.5 1810.99  4658.0 1805.08  4736.6 1794.80  4809.1 1787.68
  4844.8 1779.74  4859.5 1777.70  4871.8 1774.89  4930.8 1773.22  4957.8 1771.02
  4987.3 1771.87  4991.6 1770.61  4998.2 1770.61  5008.8 1766.92  5011.5 1764.90
  5012.0 1764.40  5034.4 1764.90  5051.3 1767.96  5065.4 1772.05  5107.8 1773.26
  5178.6 1771.97  5235.1 1774.01  5277.5 1773.32  5447.3 1775.76  5687.7 1777.49
  5829.1 1779.35  5885.7 1782.49  5956.4 1789.20  6055.4 1793.71  6126.1 1799.92
#Mann=3,-1,0
  4564.6    0.05       0  5011.5    0.03       0  5034.4    0.05       0
Bank Sta=5011.5,5034.4
Exp/Cntr=0.3,0.1

Type RM Length L Ch R = 1,55445,532,532,532
BEGIN DESCRIPTION:
Spring Creek 86.0
END DESCRIPTION:
XS GIS Cut Line= 3
      1645204.99      6891587.99      1645655.00      6892188.00
      1646158.70      6892375.27
#Sta/Elev= 30
  4249.7 1810.93  4377.8 1798.08  4421.6 1790.94  4486.2 1783.67  4513.3 1777.58
  4549.7 1773.50  4692.4 1771.19  4842.4 1771.11  4849.7 1771.26  4857.0 1773.61
  4863.3 1770.84  4871.6 1773.79  4877.8 1771.23  4886.2 1774.26  4892.4 1771.70
  4907.0 1774.51  4913.3 1772.36  4921.6 1772.03  4927.8 1769.41  4977.8 1765.85
  4985.1 1761.59  4985.6 1761.09  5008.0 1761.59  5021.1 1768.98  5039.9 1771.82
  5075.6 1771.07  5125.6 1773.32  5161.3 1771.79  5272.0 1774.97  5537.1 1777.63
#Mann=3,-1,0
  4249.7    0.05       0  4985.1    0.05       0  5008.0    0.05       0
Bank Sta=4985.1,5008
Exp/Cntr=0.3,0.1

Type RM Length L Ch R = 1,54913,573,573,573
BEGIN DESCRIPTION:
Spring Creek 85.0
END DESCRIPTION:
XS GIS Cut Line= 3
      1644905.02      6891838.04      1645155.00      6892288.00
      1645754.98      6893087.97
#Sta/Elev= 30
  4480.1 1808.44  4596.7 1795.21  4656.2 1784.74  4721.4 1770.93  4743.2 1769.69
  4811.8 1768.87  4846.1 1766.19  4862.1 1766.38  4883.9 1769.26  4949.1 1768.52
  4965.1 1767.58  4981.1 1763.30  4986.8 1763.77  4996.7 1760.65  4997.2 1760.15
  5020.1 1760.65  5031.3 1763.48  5037.5 1762.78  5052.1 1768.79  5058.4 1768.54
  5066.7 1771.78  5073.0 1772.11  5081.3 1774.37  5094.8 1774.72  5102.1 1770.76
  5137.5 1770.00  5658.4 1779.10  5837.5 1788.26  5902.1 1795.95  5994.8 1803.78
#Mann=3,-1,0
  4480.1    0.05       0  4996.7    0.03       0  5020.1    0.05       0
Bank Sta=4996.7,5020.1
Exp/Cntr=0.3,0.1

Type RM Length L Ch R = 1,54340,572,572,572
BEGIN DESCRIPTION:
Spring Creek 84.0
END DESCRIPTION:
XS GIS Cut Line= 3
      1644605.00      6892088.02      1644655.00      6892488.00
      1645105.02      6893288.03
#Sta/Elev= 30
  4596.3 1800.87  4707.1 1787.39  4757.5 1771.70  4767.6 1767.59  4776.1 1761.29
  4776.6 1760.79  4799.5 1761.29  4800.4 1763.27  4807.9 1765.32  4828.1 1766.33
  4848.2 1765.05  4868.4 1766.35  4888.5 1772.81  4938.9 1772.76  4949.0 1772.11
  4956.6 1770.30  4961.6 1772.10  4989.3 1767.89  5013.1 1766.75  5022.3 1765.34
  5045.0 1767.38  5066.6 1767.84  5153.3 1768.43  5160.0 1769.33  5196.7 1768.54
  5331.2 1769.42  5542.1 1773.69  5704.1 1781.35  5866.0 1794.05  5917.3 1797.07
#Mann=3,-1,0
  4596.3    0.05       0  4776.1    0.03       0  4799.5    0.05       0
Bank Sta=4776.1,4799.5
Exp/Cntr=0.3,0.1

Type RM Length L Ch R = 1,53768,421,421,421
BEGIN DESCRIPTION:
Spring Creek 83.0
END DESCRIPTION:
XS GIS Cut Line= 3
      1644004.98      6892137.96      1644157.08      6892497.90
      1644541.83      6893454.57
#Sta/Elev= 30
  4619.0 1802.63  4662.7 1799.36  4727.6 1795.94  4739.3 1793.95  4803.6 1787.31
  4839.5 1781.95  4868.7 1775.97  4879.6 1775.12  4886.9 1773.09  4916.0 1769.57
  4939.7 1764.97  4977.3 1762.81  4987.1 1760.63  4987.3 1758.58  4987.8 1758.08
  5010.7 1758.58  5016.4 1760.18  5021.8 1759.24  5031.4 1760.00  5040.6 1763.30
  5046.0 1762.69  5053.0 1765.25  5183.0 1766.26  5322.4 1764.44  5624.2 1768.88
  5667.3 1770.63  5785.9 1773.03  5947.6 1778.33  6001.5 1780.75  6040.9 1784.76
#Mann=3,-1,0
  4619.0    0.05       0  4987.3    0.03       0  5010.7    0.05       0
Bank Sta=4987.3,5010.7
Exp/Cntr=0.3,0.1

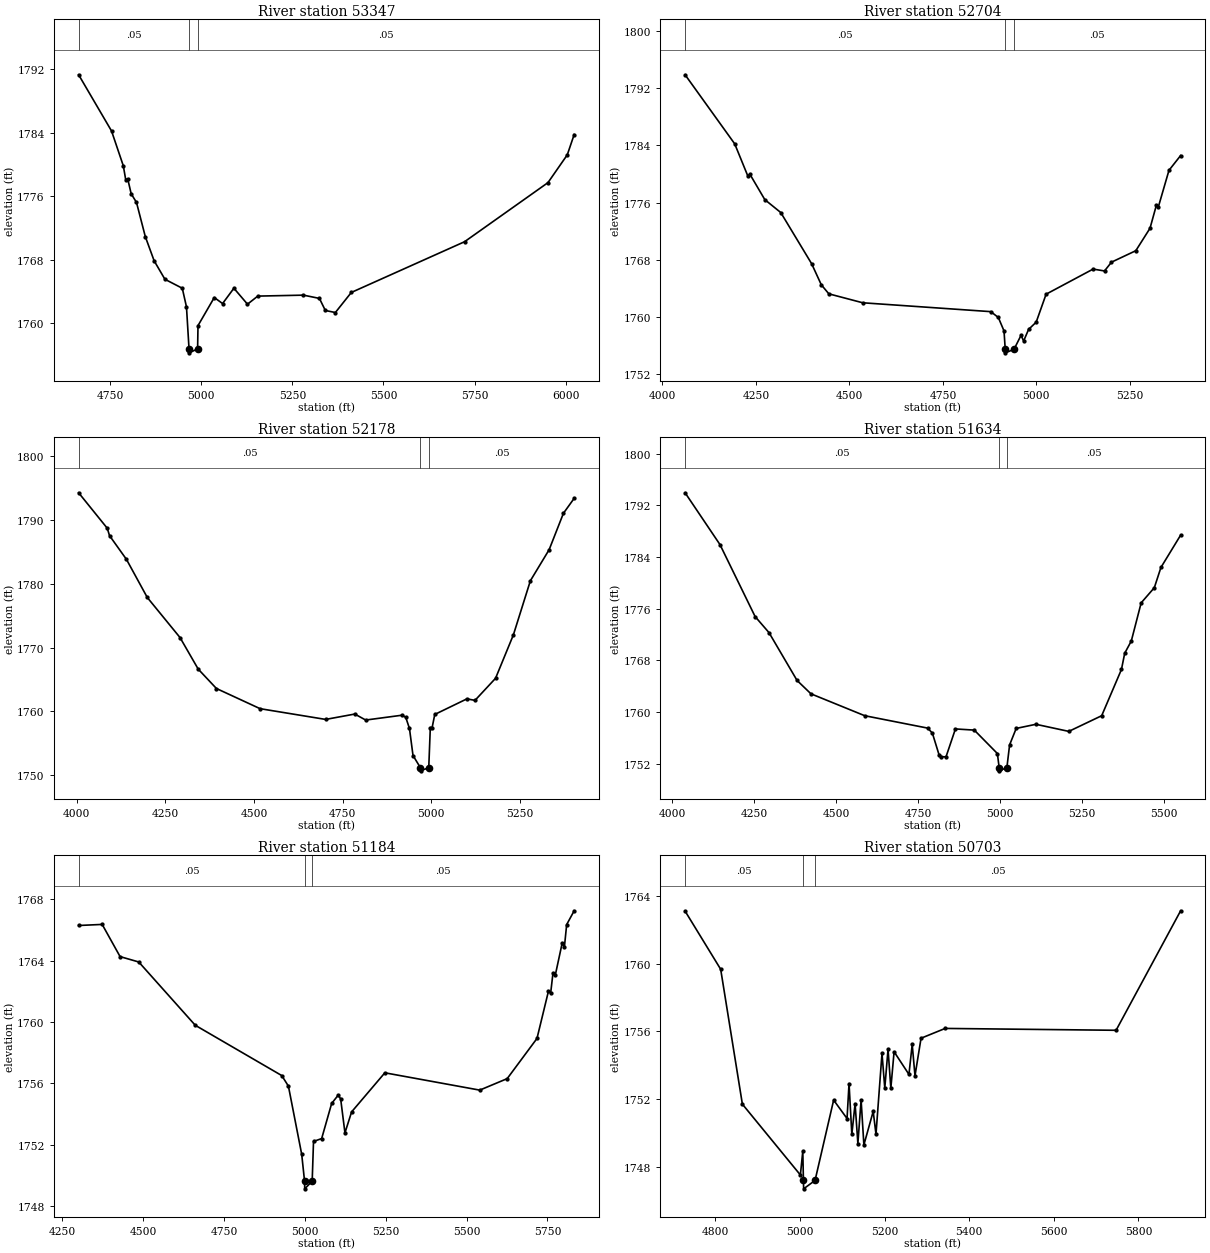
Type RM Length L Ch R = 1,53347,643,643,643
BEGIN DESCRIPTION:
Spring Creek 82.0
END DESCRIPTION:
XS GIS Cut Line= 3
      1643681.40      6892324.32      1643809.86      6892643.73
      1644295.14      6893534.56
#Sta/Elev= 30
  4664.1 1791.30  4754.3 1784.22  4786.6 1779.83  4793.2 1778.08  4798.6 1778.20
  4808.2 1776.30  4822.7 1775.22  4846.9 1770.91  4871.1 1767.86  4900.7 1765.53
  4948.3 1764.40  4959.8 1762.05  4966.8 1756.76  4967.3 1756.26  4990.3 1756.76
  4991.4 1759.69  5036.0 1763.23  5058.8 1762.47  5089.8 1764.40  5127.1 1762.39
  5155.3 1763.41  5280.6 1763.53  5324.3 1763.12  5340.5 1761.60  5368.0 1761.34
  5411.8 1763.87  5722.2 1770.26  5951.0 1777.71  6003.9 1781.21  6022.8 1783.77
#Mann=3,-1,0
  4664.1    0.05       0  4966.8    0.03       0  4990.3    0.05       0
Bank Sta=4966.8,4990.3
Exp/Cntr=0.3,0.1

Type RM Length L Ch R = 1,52704,526,526,526
BEGIN DESCRIPTION:
Mapping XS 8e6db566
END DESCRIPTION:
XS GIS Cut Line= 3
      1643400.14      6892206.27      1643500.83      6893053.45
      1643580.69      6893518.71
#Sta/Elev= 30
  4060.6 1793.87  4193.3 1784.21  4228.7 1779.67  4233.7 1779.98  4273.8 1776.41
  4316.4 1774.61  4399.0 1767.45  4424.9 1764.50  4445.0 1763.24  4535.6 1761.99
  4878.0 1760.75  4898.2 1759.94  4913.5 1758.05  4916.7 1755.49  4917.2 1754.99
  4940.3 1755.49  4958.9 1757.43  4966.0 1756.65  4979.2 1758.27  4999.5 1759.28
  5026.0 1763.19  5151.7 1766.70  5182.2 1766.44  5200.9 1767.67  5265.9 1769.27
  5303.9 1772.41  5320.9 1775.63  5325.9 1775.34  5354.6 1780.51  5385.8 1782.58
#Mann=3,-1,0
  4060.6    0.05       0  4916.7    0.03       0  4940.3    0.05       0
Bank Sta=4916.7,4940.3
Exp/Cntr=0.3,0.1

Type RM Length L Ch R = 1,52178,544,544,544
BEGIN DESCRIPTION:
Spring Creek 81.0
END DESCRIPTION:
XS GIS Cut Line= 3
      1643230.00      6892119.43      1643005.00      6893088.00
      1642955.00      6893488.03
#Sta/Elev= 30
  4005.3 1794.23  4086.0 1788.68  4092.4 1787.52  4140.1 1783.81  4198.9 1777.84
  4291.3 1771.56  4342.6 1766.62  4393.9 1763.59  4517.1 1760.43  4701.9 1758.75
  4784.1 1759.59  4814.9 1758.65  4917.5 1759.41  4927.8 1759.08  4938.3 1757.33
  4948.3 1753.10  4969.1 1751.20  4969.6 1750.70  4992.7 1751.20  4997.1 1757.47
  5002.2 1757.47  5009.7 1759.53  5100.4 1761.97  5123.1 1761.73  5181.1 1765.19
  5231.4 1771.99  5279.3 1780.46  5332.2 1785.32  5372.5 1791.02  5402.8 1793.36
#Mann=3,-1,0
  4005.3    0.05       0  4969.1    0.03       0  4992.7    0.05       0
Bank Sta=4969.1,4992.7
Exp/Cntr=0.3,0.1

Type RM Length L Ch R = 1,51634,450,450,450
BEGIN DESCRIPTION:
Spring Creek 80.0
END DESCRIPTION:
XS GIS Cut Line= 3
      1643154.99      6892088.01      1642555.00      6892838.00
      1642605.00      6893387.97
#Sta/Elev= 30
  4038.6 1793.94  4145.0 1785.92  4252.3 1774.77  4294.7 1772.28  4380.4 1764.87
  4422.8 1762.80  4586.9 1759.41  4779.0 1757.49  4793.4 1756.72  4814.2 1753.29
  4820.6 1753.07  4835.0 1753.03  4863.8 1757.36  4921.4 1757.18  4991.9 1753.55
  4997.3 1751.37  4997.8 1750.87  5020.9 1751.37  5029.2 1754.89  5049.3 1757.44
  5109.5 1758.08  5209.9 1756.98  5310.3 1759.41  5370.6 1766.57  5380.6 1769.09
  5400.7 1770.98  5430.8 1776.89  5471.0 1779.24  5491.1 1782.37  5551.3 1787.38
#Mann=3,-1,0
  4038.6    0.05       0  4997.3    0.03       0  5020.9    0.05       0
Bank Sta=4997.3,5020.9
Exp/Cntr=0.3,0.1

Type RM Length L Ch R = 1,51184,481,481,481
BEGIN DESCRIPTION:
Spring Creek 79.0
END DESCRIPTION:
XS GIS Cut Line= 3
      1642429.66      6891857.25      1642188.33      6892862.48
      1642546.00      6893209.73
#Sta/Elev= 30
  4300.5 1766.30  4373.3 1766.37  4428.7 1764.27  4486.4 1763.92  4661.2 1759.79
  4928.6 1756.51  4949.2 1755.82  4990.3 1751.37  4999.1 1749.62  4999.6 1749.12
  5022.7 1749.62  5026.8 1752.21  5052.0 1752.40  5082.9 1754.69  5103.4 1755.24
  5110.8 1754.98  5124.0 1752.77  5144.6 1754.14  5247.4 1756.69  5540.8 1755.56
  5625.7 1756.31  5717.8 1758.93  5753.1 1762.00  5760.2 1761.90  5767.2 1763.19
  5774.4 1763.06  5795.5 1765.13  5802.7 1764.92  5809.6 1766.36  5832.8 1767.26
#Mann=3,-1,0
  4300.5    0.05       0  4999.1    0.03       0  5022.7    0.05       0
Bank Sta=4999.1,5022.7
Exp/Cntr=0.3,0.1

Type RM Length L Ch R = 1,50703,121,121,121
BEGIN DESCRIPTION:
Mapping XS c954127e
END DESCRIPTION:
XS GIS Cut Line= 4
      1641713.42      6892318.88      1641829.96      6892568.61
      1641887.30      6892659.24      1642486.60      6893171.61
#Sta/Elev= 30
  4728.5 1763.12  4812.6 1759.68  4863.9 1751.70  5001.0 1747.51  5006.7 1748.92
  5008.2 1747.19  5008.7 1746.69  5035.7 1747.19  5079.6 1751.94  5111.3 1750.85
  5116.0 1752.92  5122.6 1749.91  5130.3 1751.73  5136.9 1749.37  5144.5 1751.95
  5151.1 1749.29  5173.1 1751.27  5179.7 1749.92  5193.9 1754.70  5200.5 1752.65
  5208.2 1754.95  5214.8 1752.64  5222.5 1754.80  5257.6 1753.46  5265.3 1755.23
  5271.9 1753.38  5286.2 1755.60  5343.2 1756.18  5747.2 1756.07  5899.8 1763.14
#Mann=3,-1,0
  4728.5    0.05       0  5008.2    0.03       0  5035.7    0.05       0
Bank Sta=5008.2,5035.7
Exp/Cntr=0.3,0.1

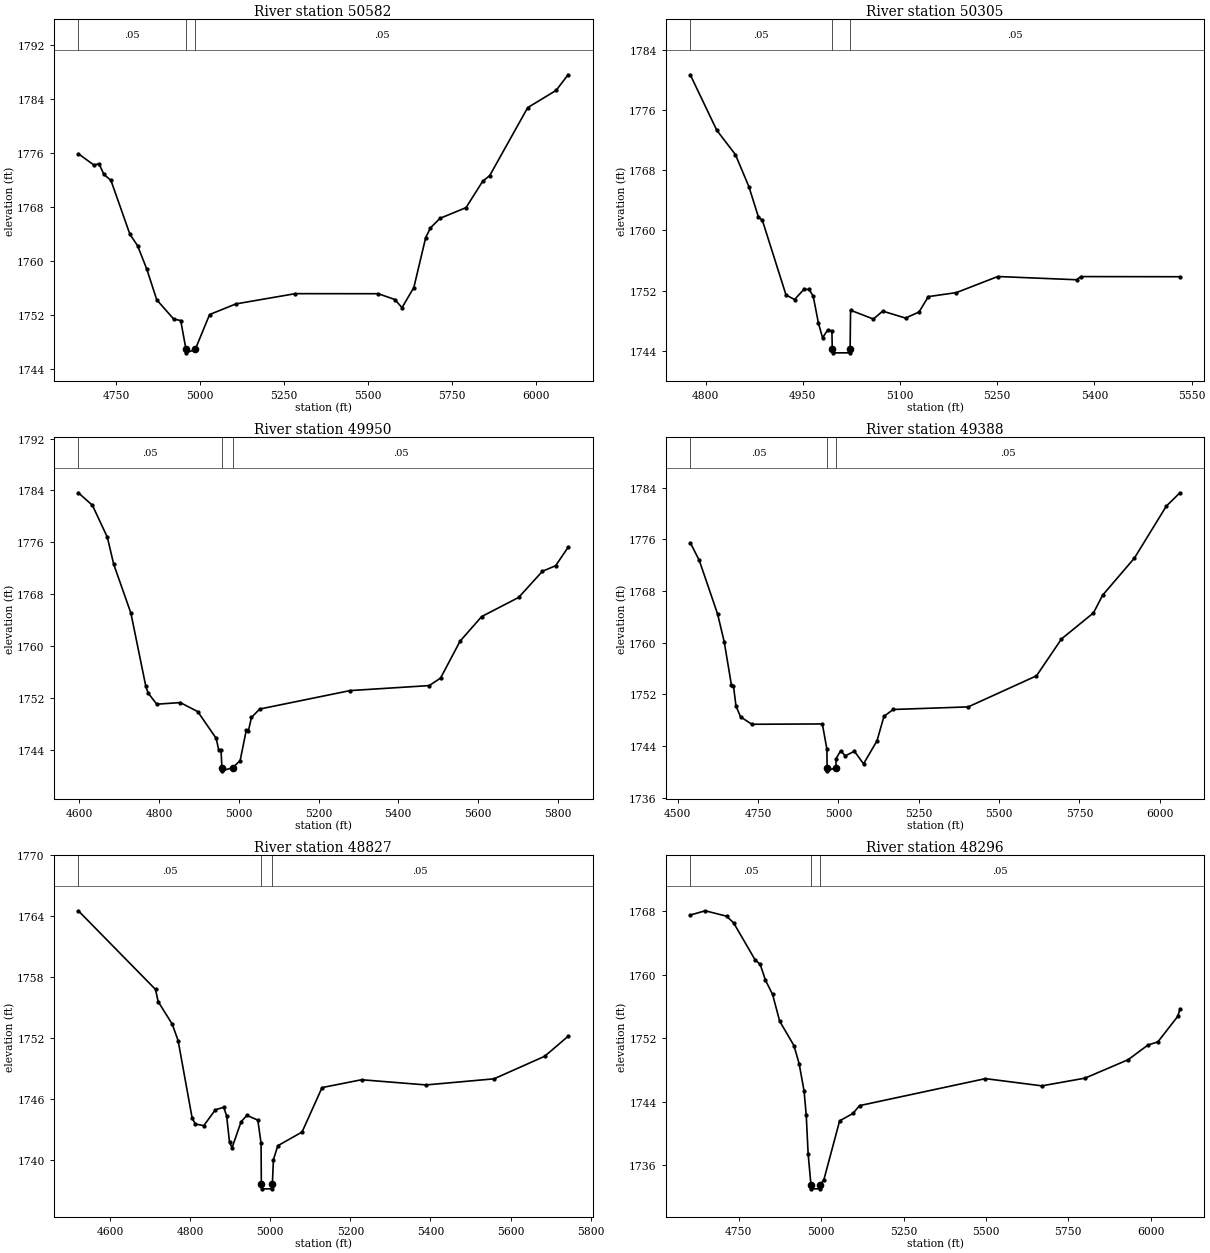
Type RM Length L Ch R = 1,50582,277,277,277
BEGIN DESCRIPTION:
Spring Creek 78.0
END DESCRIPTION:
XS GIS Cut Line= 3
      1641533.81      6892353.78      1641794.24      6892721.85
      1642505.02      6893438.02
#Sta/Elev= 30
  4637.0 1775.88  4683.7 1774.19  4698.5 1774.40  4713.3 1772.80  4734.2 1771.92
  4790.8 1763.92  4813.7 1762.23  4841.2 1758.74  4870.8 1754.20  4921.3 1751.35
  4942.2 1751.13  4958.0 1746.84  4958.5 1746.34  4985.5 1746.84  5028.3 1752.02
  5106.9 1753.60  5283.7 1755.12  5531.2 1755.11  5580.7 1754.25  5601.9 1753.04
  5637.2 1756.03  5672.6 1763.44  5686.8 1764.88  5715.1 1766.29  5792.8 1767.88
  5842.3 1771.78  5863.5 1772.64  5976.7 1782.72  6061.4 1785.27  6096.9 1787.59
#Mann=3,-1,0
  4637.0    0.05       0  4958.0    0.03       0  4985.5    0.05       0
Bank Sta=4958,4985.5
Exp/Cntr=0.3,0.1

Type RM Length L Ch R = 1,50305,355,355,355
BEGIN DESCRIPTION:
Mapping XS e4d878c9
END DESCRIPTION:
XS GIS Cut Line= 2
      1641369.88      6892655.99      1641958.92      6893129.08
#Sta/Elev= 30
  4776.5 1780.66  4817.4 1773.29  4846.2 1770.05  4867.0 1765.79  4881.4 1761.83
  4887.8 1761.31  4924.2 1751.41  4937.4 1750.80  4951.8 1752.15  4959.8 1752.15
  4966.2 1751.24  4974.2 1747.68  4980.6 1745.72  4988.3 1746.73  4995.0 1746.65
  4995.6 1744.22  4996.1 1743.72  5022.6 1743.72  5023.1 1744.22  5023.8 1749.38
  5059.0 1748.21  5073.4 1749.26  5108.6 1748.34  5129.4 1749.14  5143.8 1751.19
  5187.0 1751.72  5251.0 1753.86  5372.6 1753.43  5379.0 1753.85  5532.0 1753.83
#Mann=3,-1,0
  4776.5    0.05       0  4995.6    0.03       0  5023.1    0.05       0
Bank Sta=4995.6,5023.1
Exp/Cntr=0.3,0.1

Type RM Length L Ch R = 1,49950,562,562,562
BEGIN DESCRIPTION:
Spring Creek 77.0
END DESCRIPTION:
XS GIS Cut Line= 3
      1641154.96      6892937.98      1641505.00      6893138.00
      1642305.02      6893338.01
#Sta/Elev= 30
  4597.8 1783.63  4633.1 1781.70  4670.5 1776.78  4686.4 1772.62  4729.6 1765.06
  4767.0 1753.77  4772.8 1752.74  4794.4 1751.02  4853.4 1751.27  4897.3 1749.87
  4943.4 1745.75  4949.8 1743.94  4955.6 1743.97  4957.7 1741.24  4958.2 1740.74
  4985.2 1741.24  5003.5 1742.33  5019.0 1747.04  5024.1 1746.89  5031.9 1748.98
  5052.5 1750.27  5279.3 1753.12  5477.7 1753.89  5506.0 1755.05  5555.0 1760.75
  5609.1 1764.54  5701.9 1767.49  5761.2 1771.51  5794.7 1772.39  5825.6 1775.21
#Mann=3,-1,0
  4597.8    0.05       0  4957.7    0.05       0  4985.2    0.05       0
Bank Sta=4957.7,4985.2
Exp/Cntr=0.3,0.1

Type RM Length L Ch R = 1,49388,561,561,561
BEGIN DESCRIPTION:
Spring Creek 76.0
END DESCRIPTION:
XS GIS Cut Line= 3
      1641004.98      6893337.98      1641355.00      6893638.00
      1642154.99      6894337.99
#Sta/Elev= 30
  4538.7 1775.48  4566.7 1772.75  4623.8 1764.43  4644.6 1760.07  4666.6 1753.49
  4673.2 1753.30  4680.9 1750.21  4695.1 1748.53  4730.3 1747.37  4949.8 1747.42
  4964.0 1743.49  4964.5 1740.66  4965.0 1740.16  4992.1 1740.66  4992.6 1742.06
  5006.8 1743.28  5021.1 1742.48  5049.5 1743.19  5078.0 1741.24  5119.8 1744.81
  5141.6 1748.60  5170.1 1749.66  5403.6 1750.06  5616.2 1754.87  5694.0 1760.58
  5793.6 1764.62  5822.1 1767.36  5920.8 1773.09  6020.5 1781.16  6062.7 1783.21
#Mann=3,-1,0
  4538.7    0.05       0  4964.5    0.03       0  4992.1    0.05       0
Bank Sta=4964.5,4992.1
Exp/Cntr=0.3,0.1

Type RM Length L Ch R = 1,48827,531,531,531
BEGIN DESCRIPTION:
Spring Creek 75.0
END DESCRIPTION:
XS GIS Cut Line= 3
      1640707.41      6893655.86      1641005.00      6894038.00
      1641658.79      6894381.56
#Sta/Elev= 30
  4520.6 1764.53  4713.4 1756.79  4719.9 1755.60  4755.2 1753.37  4769.7 1751.77
  4805.0 1744.10  4813.1 1743.55  4833.9 1743.40  4862.9 1744.96  4883.7 1745.20
  4890.9 1744.35  4898.2 1741.74  4904.5 1741.23  4927.1 1743.78  4941.6 1744.41
  4968.8 1743.94  4976.9 1741.67  4977.6 1737.68  4978.1 1737.18  5004.7 1737.18
  5005.2 1737.68  5007.8 1740.06  5018.8 1741.42  5079.3 1742.77  5129.2 1747.14
  5227.9 1747.91  5389.0 1747.40  5558.6 1748.00  5685.2 1750.22  5743.5 1752.18
#Mann=3,-1,0
  4520.6    0.05       0  4977.6    0.05       0  5005.2    0.05       0
Bank Sta=4977.6,5005.2
Exp/Cntr=0.3,0.1

Type RM Length L Ch R = 1,48296,419,419,419
BEGIN DESCRIPTION:
Spring Creek 74.0
END DESCRIPTION:
XS GIS Cut Line= 3
      1640405.01      6893988.02      1640605.00      6894338.00
      1641681.56      6894457.79
#Sta/Elev= 30
  4602.6 1767.51  4647.9 1768.05  4712.7 1767.37  4734.3 1766.52  4799.1 1761.89
  4814.9 1761.30  4830.8 1759.31  4852.4 1757.52  4874.0 1754.14  4917.2 1751.08
  4933.0 1748.80  4948.1 1745.33  4954.6 1742.29  4960.3 1737.48  4968.9 1733.53
  4969.4 1733.03  4996.0 1733.03  4996.5 1733.53  5008.2 1734.19  5056.0 1741.60
  5096.3 1742.52  5116.4 1743.51  5498.4 1746.91  5669.8 1746.00  5800.6 1746.97
  5931.4 1749.29  5991.7 1751.14  6021.9 1751.54  6082.3 1754.76  6088.9 1755.68
#Mann=3,-1,0
  4602.6    0.05       0  4968.9    0.05       0  4996.5    0.05       0
Bank Sta=4968.9,4996.5
Exp/Cntr=0.3,0.1

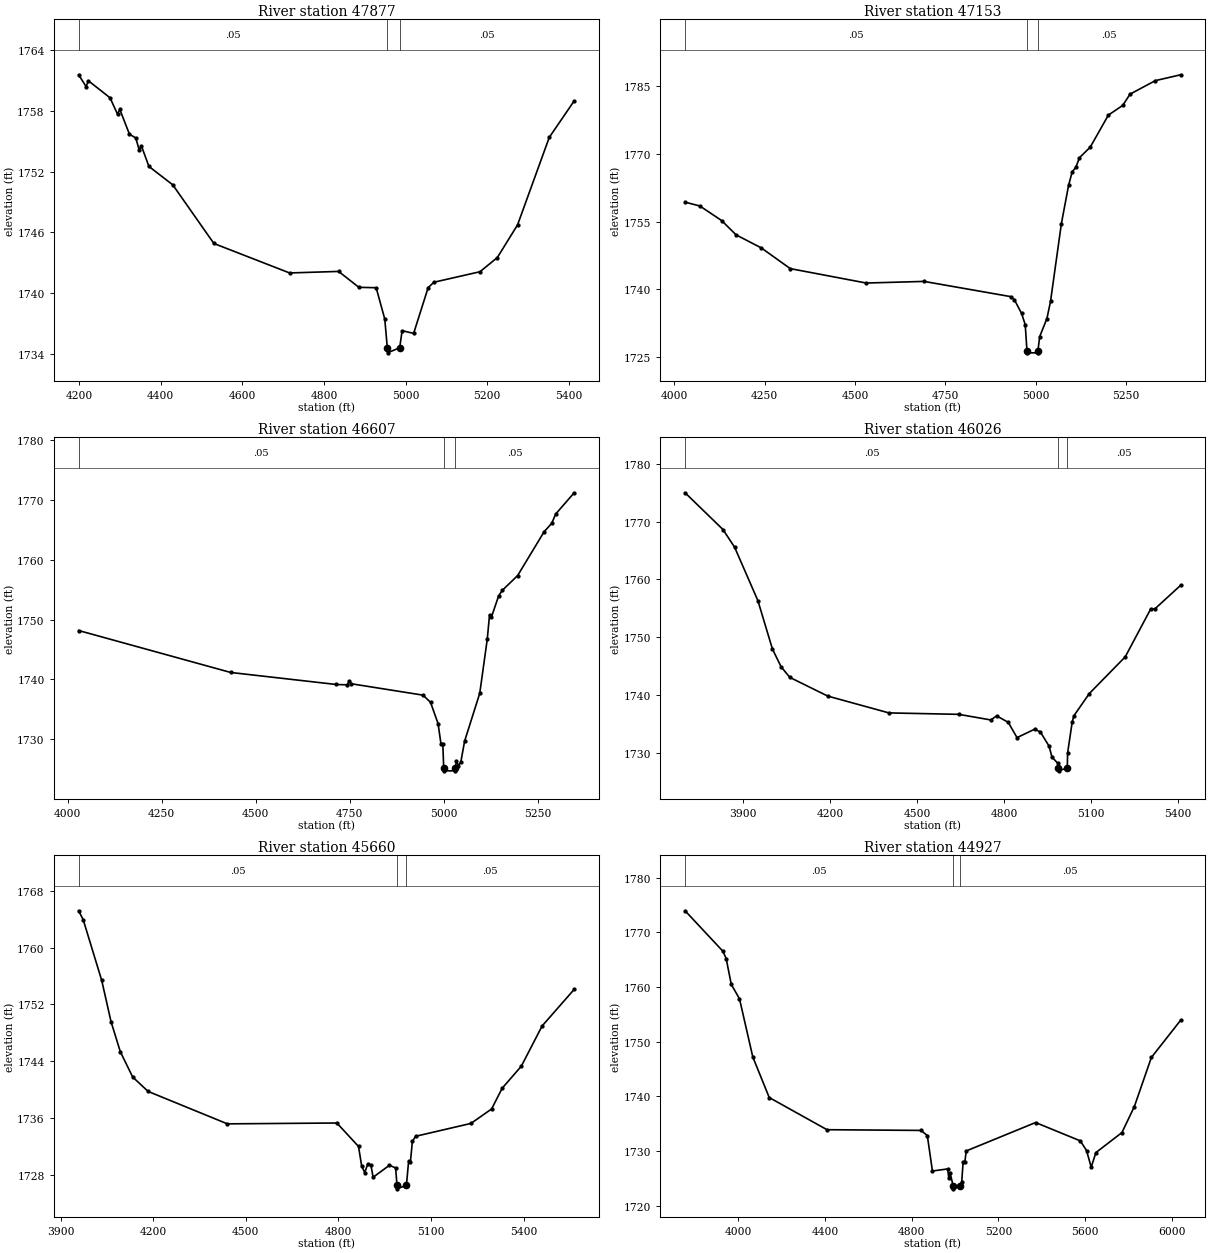
Type RM Length L Ch R = 1,47877,724,724,724
BEGIN DESCRIPTION:
Mapping XS dd40da45
END DESCRIPTION:
XS GIS Cut Line= 3
      1640151.87      6894058.64      1640290.76      6894391.99
      1640900.94      6894988.30
#Sta/Elev= 30
  4198.7 1761.57  4217.1 1760.40  4222.5 1760.98  4275.6 1759.30  4294.0 1757.68
  4299.4 1758.17  4323.2 1755.70  4338.8 1755.33  4347.1 1754.14  4352.5 1754.55
  4370.9 1752.52  4429.4 1750.70  4530.1 1744.91  4715.6 1742.00  4835.8 1742.15
  4885.4 1740.58  4927.8 1740.54  4948.9 1737.44  4955.1 1734.61  4955.6 1734.11
  4985.4 1734.61  4991.4 1736.30  5019.6 1736.03  5055.1 1740.54  5069.1 1741.08
  5182.2 1742.12  5224.7 1743.52  5274.3 1746.75  5352.0 1755.39  5413.0 1758.99
#Mann=3,-1,0
  4198.7    0.05       0  4955.1    0.05       0  4985.4    0.05       0
Bank Sta=4955.1,4985.4
Exp/Cntr=0.3,0.1

Type RM Length L Ch R = 1,47153,546,546,546
BEGIN DESCRIPTION:
Spring Creek 73.0
END DESCRIPTION:
XS GIS Cut Line= 3
      1640072.01      6894017.01      1640055.00      6894988.00
      1640055.00      6895387.96
#Sta/Elev= 30
  4030.0 1759.31  4071.0 1758.45  4131.0 1755.23  4171.0 1752.05  4241.0 1749.14
  4321.0 1744.55  4531.1 1741.35  4691.1 1741.71  4931.1 1738.33  4941.1 1737.64
  4961.1 1734.59  4971.1 1732.10  4975.9 1726.35  4976.4 1725.85  5005.8 1725.85
  5006.3 1726.35  5011.1 1729.46  5031.1 1733.46  5041.1 1737.28  5071.1 1754.52
  5091.1 1763.06  5101.1 1766.05  5111.1 1767.03  5121.1 1769.17  5151.1 1771.54
  5201.1 1778.63  5241.1 1780.81  5261.1 1783.29  5331.1 1786.29  5401.1 1787.59
#Mann=3,-1,0
  4030.0    0.05       0  4975.9    0.05       0  5006.3    0.05       0
Bank Sta=4975.9,5006.3
Exp/Cntr=0.3,0.1

Type RM Length L Ch R = 1,46607,581,581,581
BEGIN DESCRIPTION:
Spring Creek 72.0
END DESCRIPTION:
XS GIS Cut Line= 3
      1639613.68      6893874.60      1639555.00      6894838.00
      1639596.32      6895187.18
#Sta/Elev= 30
  4029.4 1748.18  4433.5 1741.17  4714.1 1739.16  4743.5 1739.10  4748.5 1739.75
  4754.1 1739.28  4944.5 1737.38  4964.5 1736.18  4984.6 1732.61  4992.1 1729.29
  4997.1 1729.29  4999.5 1725.23  5000.0 1724.73  5029.4 1724.73  5029.9 1725.23
  5033.5 1726.30  5038.5 1725.62  5044.9 1726.16  5055.0 1729.68  5095.3 1737.69
  5115.4 1746.80  5121.3 1750.83  5126.4 1750.44  5145.6 1753.99  5155.7 1754.92
  5196.0 1757.37  5266.5 1764.70  5286.6 1766.10  5297.1 1767.65  5346.2 1771.20
#Mann=3,-1,0
  4029.4    0.05       0  4999.5    0.05       0  5029.9    0.05       0
Bank Sta=4999.5,5029.9
Exp/Cntr=0.3,0.1

Type RM Length L Ch R = 1,46026,366,366,366
BEGIN DESCRIPTION:
Spring Creek 71.0
END DESCRIPTION:
XS GIS Cut Line= 3
      1638905.00      6893637.96      1639005.00      6894938.00
      1639205.00      6895288.00
#Sta/Elev= 30
  3701.4 1774.98  3831.8 1768.62  3871.9 1765.56  3952.2 1756.30  4002.3 1747.92
  4032.4 1744.83  4062.5 1743.01  4192.9 1739.78  4403.5 1736.87  4644.2 1736.62
  4754.5 1735.65  4774.6 1736.36  4814.7 1735.23  4844.8 1732.59  4905.0 1734.04
  4925.0 1733.59  4955.1 1731.12  4965.2 1729.22  4985.2 1728.15  4987.5 1727.34
  4988.0 1726.84  5018.0 1727.34  5019.0 1729.91  5034.8 1735.27  5040.6 1736.37
  5093.8 1740.22  5217.6 1746.58  5304.7 1754.81  5319.9 1754.89  5408.4 1758.96
#Mann=3,-1,0
  3701.4    0.05       0  4987.5    0.05       0  5018.0    0.05       0
Bank Sta=4987.5,5018
Exp/Cntr=0.3,0.1

Type RM Length L Ch R = 1,45660,733,733,733
BEGIN DESCRIPTION:
Spring Creek 70.0
END DESCRIPTION:
XS GIS Cut Line= 3
      1638589.37      6893843.34      1638655.35      6894881.58
      1638904.98      6895387.96
#Sta/Elev= 30
  3958.6 1765.18  3973.4 1763.93  4033.4 1755.38  4063.5 1749.59  4093.5 1745.37
  4133.6 1741.80  4183.7 1739.77  4440.4 1735.21  4794.9 1735.33  4865.1 1732.03
  4875.1 1729.32  4885.1 1728.34  4895.1 1729.58  4905.2 1729.40  4912.4 1727.70
  4965.3 1729.39  4985.3 1729.00  4989.7 1726.57  4990.2 1726.07  5020.2 1726.57
  5027.4 1730.00  5033.0 1729.78  5039.5 1732.74  5049.9 1733.46  5229.1 1735.27
  5296.0 1737.30  5330.5 1740.23  5392.3 1743.32  5459.7 1748.98  5563.5 1754.12
#Mann=3,-1,0
  3958.6    0.05       0  4989.7    0.03       0  5020.2    0.05       0
Bank Sta=4989.7,5020.2
Exp/Cntr=0.3,0.1

Type RM Length L Ch R = 1,44927,256,256,256
BEGIN DESCRIPTION:
Spring Creek 69.0
END DESCRIPTION:
XS GIS Cut Line= 3
      1638554.98      6893688.04      1638055.00      6894838.00
      1638854.98      6895487.99
#Sta/Elev= 30
  3755.4 1773.94  3929.8 1766.54  3944.8 1765.20  3968.3 1760.48  4006.1 1757.86
  4067.5 1747.22  4143.3 1739.80  4409.6 1733.92  4843.3 1733.79  4872.2 1732.84
  4895.7 1726.37  4965.7 1726.75  4971.5 1725.02  4976.9 1726.08  4991.4 1723.61
  4991.9 1723.11  5021.9 1723.61  5030.9 1724.42  5037.3 1728.08  5045.3 1728.08
  5051.7 1730.04  5371.4 1735.23  5577.5 1731.88  5606.3 1730.11  5627.8 1727.06
  5649.4 1729.74  5769.5 1733.40  5826.8 1738.16  5905.1 1747.12  6040.1 1753.93
#Mann=3,-1,0
  3755.4    0.05       0  4991.4    0.03       0  5021.9    0.05       0
Bank Sta=4991.4,5021.9
Exp/Cntr=0.3,0.1