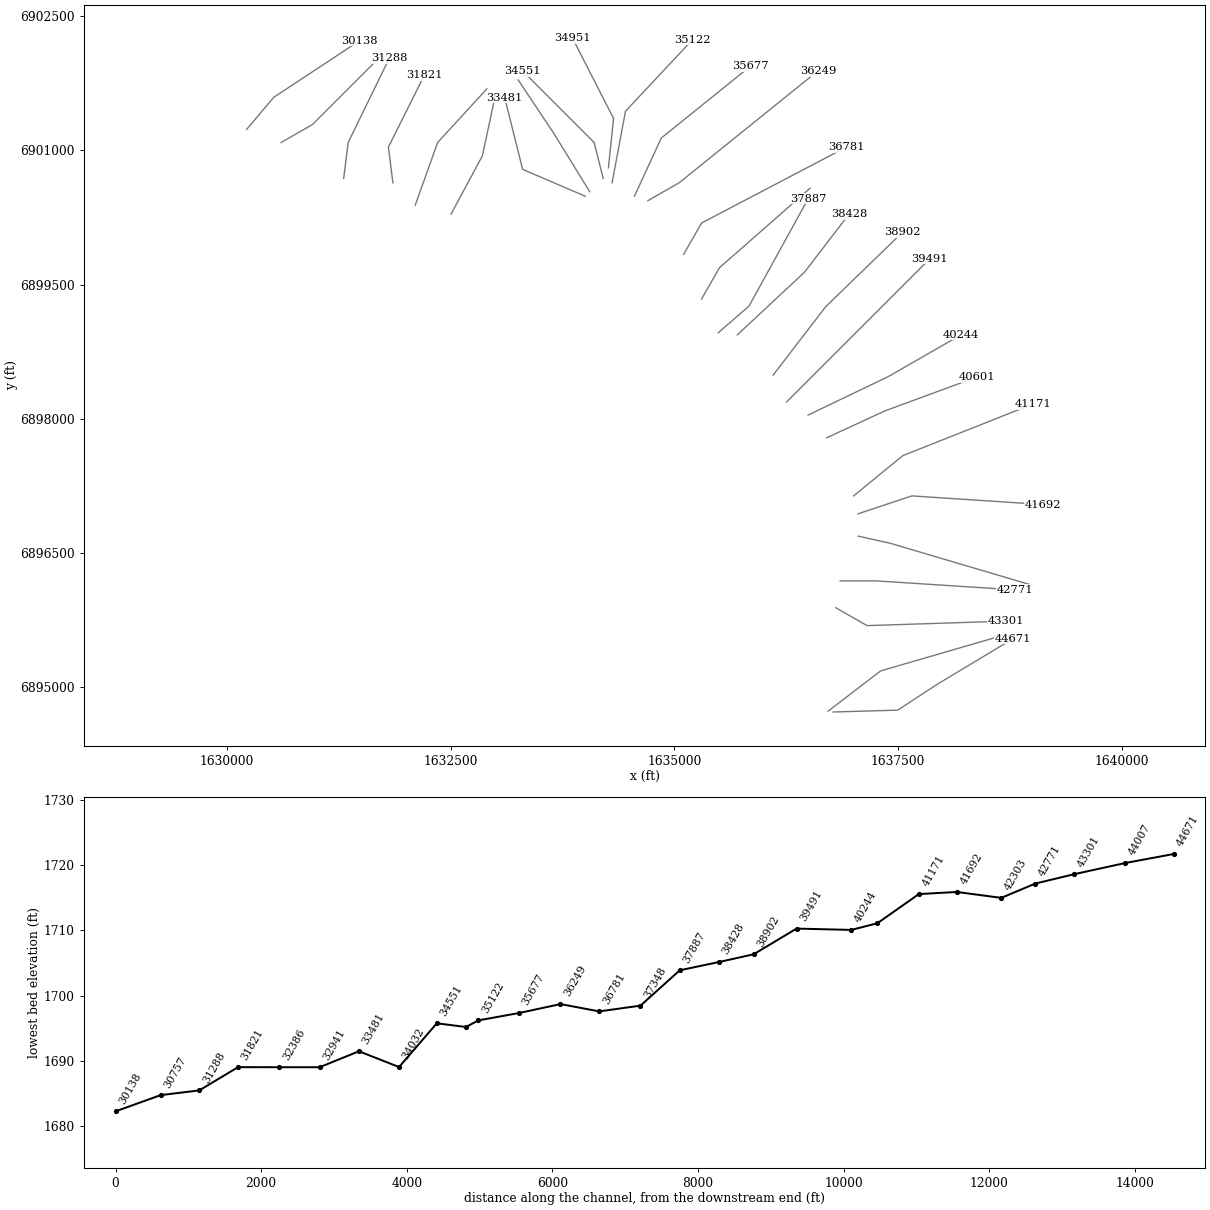
HEC-RAS study Spring Creek.prj: Spring Creek Base Level Engineering

--- Spring Creek.g01 (geometry) --- (continued)

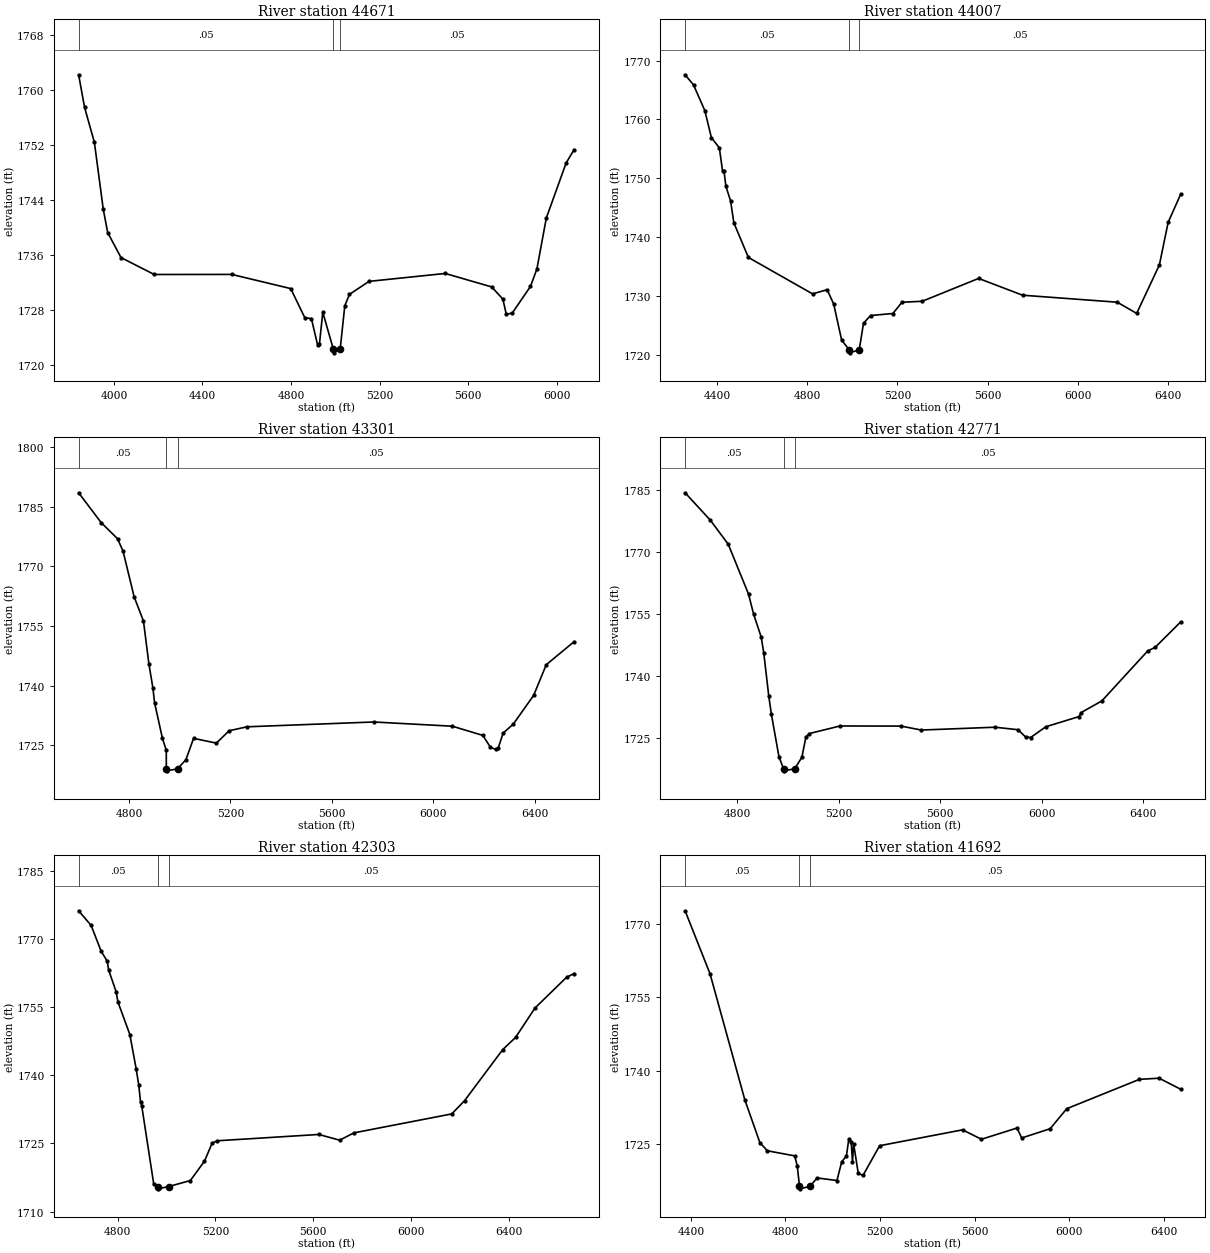
Type RM Length L Ch R = 1,44671,664,664,664
BEGIN DESCRIPTION:
Mapping XS edc7574a
END DESCRIPTION:
XS GIS Cut Line= 4
      1636773.82      6894722.23      1637497.73      6894743.06
      1637935.23      6895029.52      1638784.16      6895539.91
#Sta/Elev= 30
  3840.8 1762.20  3867.4 1757.49  3912.0 1752.35  3952.0 1742.64  3972.0 1739.24
  4032.1 1735.60  4182.1 1733.14  4532.3 1733.15  4798.5 1731.09  4861.8 1726.87
  4892.0 1726.71  4920.3 1722.83  4928.2 1722.99  4943.3 1727.65  4991.3 1722.24
  4991.8 1721.74  5021.8 1722.24  5042.7 1728.59  5063.8 1730.25  5152.4 1732.14
  5496.1 1733.29  5706.1 1731.33  5756.6 1729.55  5772.1 1727.33  5799.4 1727.55
  5881.1 1731.40  5910.1 1733.93  5952.8 1741.37  6042.2 1749.37  6078.5 1751.32
#Mann=3,-1,0
  3840.8    0.05       0  4991.3    0.05       0  5021.8    0.05       0
Bank Sta=4991.3,5021.8
Exp/Cntr=0.3,0.1

Type RM Length L Ch R = 1,44007,706,706,706
BEGIN DESCRIPTION:
Spring Creek 68.0
END DESCRIPTION:
XS GIS Cut Line= 3
      1636718.99      6894731.04      1637307.18      6895181.88
      1638704.98      6895587.99
#Sta/Elev= 30
  4258.9 1767.59  4296.5 1765.86  4346.3 1761.51  4375.4 1756.92  4410.7 1755.18
  4425.2 1751.17  4431.5 1751.18  4439.8 1748.65  4460.6 1746.16  4475.1 1742.43
  4539.5 1736.56  4824.1 1730.37  4888.5 1731.09  4917.5 1728.66  4952.8 1722.53
  4986.7 1720.86  4987.7 1720.36  5030.7 1720.86  5049.8 1725.38  5081.0 1726.70
  5180.0 1727.04  5220.3 1728.95  5310.1 1729.12  5560.1 1733.00  5754.7 1730.15
  6174.5 1728.96  6260.7 1727.06  6361.4 1735.29  6400.1 1742.51  6455.6 1747.29
#Mann=3,-1,0
  4258.9    0.05       0  4986.7    0.05       0  5030.7    0.05       0
Bank Sta=4986.7,5030.7
Exp/Cntr=0.3,0.1

Type RM Length L Ch R = 1,43301,530,530,530
BEGIN DESCRIPTION:
Spring Creek 67.0
END DESCRIPTION:
XS GIS Cut Line= 3
      1636804.98      6895888.01      1637155.00      6895688.00
      1638704.96      6895738.00
#Sta/Elev= 30
  4601.6 1788.47  4690.2 1781.00  4755.0 1776.93  4776.5 1773.86  4820.5 1762.33
  4857.2 1756.26  4878.8 1745.44  4894.6 1739.37  4901.1 1735.72  4932.0 1726.79
  4947.2 1723.79  4947.4 1719.13  4948.4 1718.63  4991.5 1719.13  5024.7 1721.44
  5054.8 1726.79  5144.8 1725.59  5194.8 1728.69  5264.9 1729.69  5765.1 1730.90
  6075.3 1729.84  6195.4 1727.53  6225.4 1724.54  6245.4 1724.03  6255.4 1724.25
  6275.4 1728.11  6315.4 1730.36  6395.5 1737.56  6445.5 1745.29  6555.5 1751.09
#Mann=3,-1,0
  4601.6    0.05       0  4947.4    0.03       0  4991.5    0.05       0
Bank Sta=4947.4,4991.5
Exp/Cntr=0.3,0.1

Type RM Length L Ch R = 1,42771,468,468,468
BEGIN DESCRIPTION:
Spring Creek 66.0
END DESCRIPTION:
XS GIS Cut Line= 3
      1636854.98      6896188.00      1637255.00      6896188.00
      1638804.96      6896088.00
#Sta/Elev= 30
  4594.5 1784.26  4694.5 1777.61  4764.5 1771.85  4844.5 1759.83  4864.5 1755.00
  4894.5 1749.46  4904.5 1745.65  4924.5 1735.14  4934.5 1730.89  4964.5 1720.59
  4982.5 1717.70  4983.5 1717.20  5026.6 1717.70  5054.6 1720.45  5070.9 1725.39
  5084.7 1726.20  5205.0 1728.02  5445.5 1727.99  5525.6 1727.04  5816.2 1727.72
  5906.4 1727.12  5936.5 1725.38  5956.5 1725.24  6016.6 1727.84  6146.9 1730.28
  6155.7 1731.26  6237.1 1734.06  6417.5 1746.09  6447.5 1747.00  6547.7 1753.10
#Mann=3,-1,0
  4594.5    0.05       0  4982.5    0.05       0  5026.6    0.05       0
Bank Sta=4982.5,5026.6
Exp/Cntr=0.3,0.1

Type RM Length L Ch R = 1,42303,611,611,611
BEGIN DESCRIPTION:
Spring Creek 65.0
END DESCRIPTION:
XS GIS Cut Line= 3
      1637055.03      6896687.99      1637405.35      6896610.74
      1639005.02      6896137.99
#Sta/Elev= 30
  4640.8 1776.26  4692.0 1773.03  4732.9 1767.34  4757.7 1765.16  4763.7 1763.19
  4794.4 1758.39  4801.4 1756.20  4850.2 1749.00  4876.3 1741.38  4886.5 1737.93
  4893.9 1734.17  4899.0 1733.25  4948.0 1716.04  4964.4 1715.50  4965.4 1715.00
  5008.5 1715.50  5097.8 1716.83  5155.6 1721.10  5186.9 1725.08  5208.1 1725.59
  5623.2 1726.98  5708.2 1725.72  5766.7 1727.33  6167.1 1731.51  6219.2 1734.42
  6375.6 1745.69  6427.7 1748.35  6507.4 1754.84  6636.3 1761.60  6667.6 1762.44
#Mann=3,-1,0
  4640.8    0.05       0  4964.4    0.05       0  5008.5    0.05       0
Bank Sta=4964.4,5008.5
Exp/Cntr=0.3,0.1

Type RM Length L Ch R = 1,41692,521,521,521
BEGIN DESCRIPTION:
Spring Creek 64.0
END DESCRIPTION:
XS GIS Cut Line= 3
      1637054.96      6896937.99      1637655.00      6897138.00
      1639115.83      6897041.67
#Sta/Elev= 30
  4375.6 1772.61  4481.1 1759.76  4628.6 1734.01  4691.9 1725.35  4723.5 1723.67
  4839.4 1722.63  4850.0 1720.62  4859.6 1716.41  4860.6 1715.91  4903.7 1716.41
  4934.3 1718.13  5018.1 1717.61  5038.2 1721.44  5058.2 1722.61  5068.2 1726.07
  5078.3 1725.53  5083.7 1721.44  5088.7 1725.05  5108.3 1719.04  5128.4 1718.66
  5198.5 1724.70  5549.3 1727.94  5629.4 1726.02  5779.8 1728.31  5799.8 1726.28
  5920.1 1728.17  5990.2 1732.25  6297.9 1738.24  6381.1 1738.47  6472.1 1736.22
#Mann=3,-1,0
  4375.6    0.05       0  4859.6    0.03       0  4903.7    0.05       0
Bank Sta=4859.6,4903.7
Exp/Cntr=0.3,0.1

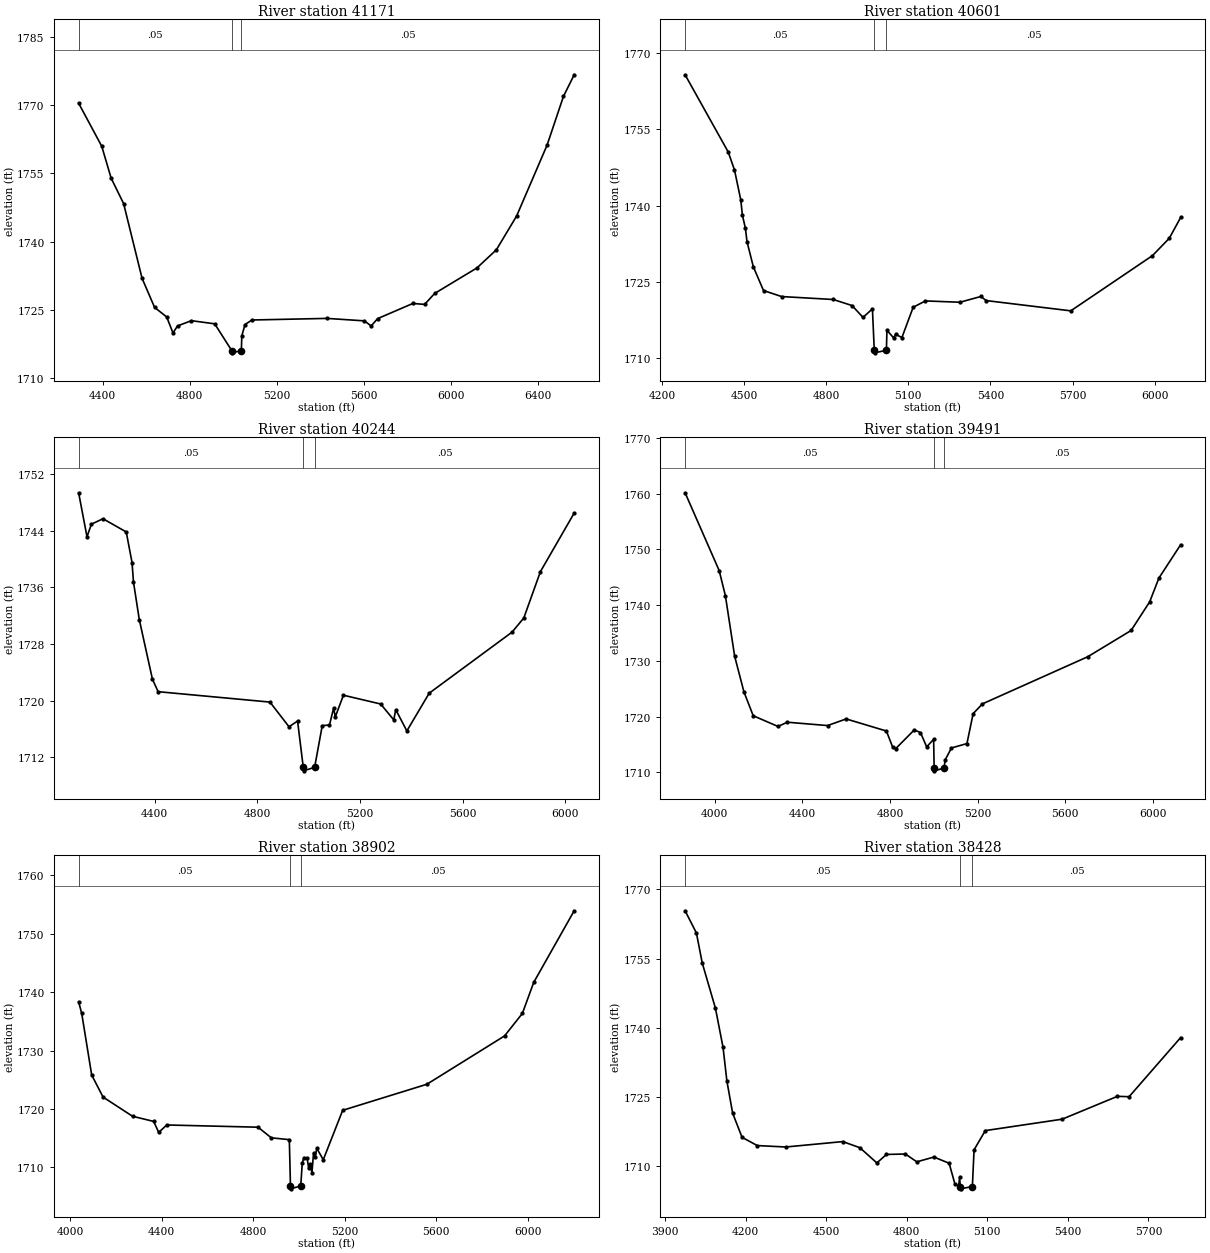
Type RM Length L Ch R = 1,41171,570,570,570
BEGIN DESCRIPTION:
Spring Creek 63.0
END DESCRIPTION:
XS GIS Cut Line= 3
      1637005.01      6897138.01      1637555.00      6897588.00
      1639010.83      6898165.48
#Sta/Elev= 30
  4289.6 1770.38  4395.8 1760.93  4438.9 1753.93  4496.3 1748.34  4581.0 1731.95
  4638.4 1725.57  4694.4 1723.44  4723.1 1719.94  4744.0 1721.49  4807.8 1722.64
  4914.8 1721.95  4993.0 1716.08  4994.0 1715.58  5037.2 1716.08  5039.4 1719.32
  5054.0 1721.80  5086.3 1722.79  5430.5 1723.14  5602.7 1722.60  5633.6 1721.48
  5663.3 1723.09  5825.3 1726.42  5879.3 1726.21  5925.4 1728.62  6119.1 1734.20
  6208.8 1738.19  6301.9 1745.61  6441.8 1761.16  6517.1 1771.87  6566.4 1776.62
#Mann=3,-1,0
  4289.6    0.05       0  4993.0    0.03       0  5037.2    0.05       0
Bank Sta=4993,5037.2
Exp/Cntr=0.3,0.1

Type RM Length L Ch R = 1,40601,357,357,357
BEGIN DESCRIPTION:
Spring Creek 62.0
END DESCRIPTION:
XS GIS Cut Line= 3
      1636705.00      6897788.00      1637355.00      6898088.00
      1638381.57      6898466.43
#Sta/Elev= 30
  4284.6 1765.73  4442.0 1750.57  4465.0 1747.04  4487.9 1741.16  4493.9 1738.16
  4504.9 1735.56  4510.8 1732.93  4533.8 1728.01  4571.0 1723.34  4637.0 1722.16
  4825.7 1721.58  4894.5 1720.39  4934.4 1718.06  4968.8 1719.74  4975.6 1711.60
  4976.6 1711.10  5019.9 1711.60  5021.8 1715.53  5046.2 1714.05  5053.8 1714.72
  5076.6 1714.11  5117.7 1720.06  5162.6 1721.30  5288.3 1721.04  5365.0 1722.17
  5384.2 1721.37  5693.3 1719.35  5991.7 1730.20  6053.0 1733.60  6094.6 1737.69
#Mann=3,-1,0
  4284.6    0.05       0  4975.6    0.05       0  5019.9    0.05       0
Bank Sta=4975.6,5019.9
Exp/Cntr=0.3,0.1

Type RM Length L Ch R = 1,40244,753,753,753
BEGIN DESCRIPTION:
Spring Creek 61.0
END DESCRIPTION:
XS GIS Cut Line= 3
      1636495.63      6898041.30      1637393.57      6898472.22
      1638205.01      6898938.00
#Sta/Elev= 30
  4103.1 1749.39  4135.7 1743.17  4152.8 1744.95  4198.1 1745.72  4288.7 1743.85
  4311.3 1739.52  4316.9 1736.76  4339.5 1731.47  4390.8 1723.03  4413.0 1721.27
  4848.9 1719.80  4923.2 1716.31  4956.5 1717.12  4978.7 1710.58  4979.7 1710.08
  5023.0 1710.58  5052.7 1716.47  5080.9 1716.56  5097.1 1718.95  5103.6 1717.71
  5135.2 1720.77  5280.4 1719.53  5331.3 1717.29  5339.4 1718.72  5382.5 1715.72
  5469.7 1721.06  5792.6 1729.69  5838.4 1731.69  5903.1 1738.24  6034.7 1746.52
#Mann=3,-1,0
  4103.1    0.05       0  4978.7    0.05       0  5023.0    0.05       0
Bank Sta=4978.7,5023
Exp/Cntr=0.3,0.1

Type RM Length L Ch R = 1,39491,589,589,589
BEGIN DESCRIPTION:
Spring Creek 60.0
END DESCRIPTION:
XS GIS Cut Line= 3
      1636254.99      6898187.99      1637055.00      6898988.00
      1637855.03      6899788.03
#Sta/Elev= 30
  3864.2 1760.15  4019.8 1746.20  4048.1 1741.71  4090.5 1730.83  4132.9 1724.44
  4175.3 1720.16  4288.5 1718.24  4330.9 1719.00  4514.8 1718.40  4599.6 1719.59
  4783.5 1717.42  4811.7 1714.56  4825.9 1714.26  4910.7 1717.62  4939.0 1717.15
  4967.3 1714.58  4999.1 1715.93  5001.4 1710.78  5002.4 1710.28  5046.3 1710.78
  5052.2 1712.27  5080.4 1714.38  5151.2 1715.17  5179.4 1720.53  5221.9 1722.29
  5702.7 1730.74  5900.7 1735.45  5985.5 1740.58  6028.0 1744.87  6127.0 1750.83
#Mann=3,-1,0
  3864.2    0.05       0  5001.4    0.03       0  5046.3    0.05       0
Bank Sta=5001.4,5046.3
Exp/Cntr=0.3,0.1

Type RM Length L Ch R = 1,38902,474,474,474
BEGIN DESCRIPTION:
Spring Creek 59.0
END DESCRIPTION:
XS GIS Cut Line= 3
      1636105.02      6898488.03      1636691.59      6899251.52
      1637555.03      6900088.03
#Sta/Elev= 30
  4037.2 1738.33  4050.7 1736.35  4094.3 1725.80  4144.1 1722.03  4272.8 1718.75
  4365.0 1717.87  4387.0 1715.99  4422.3 1717.26  4821.1 1716.88  4879.1 1715.06
  4957.7 1714.75  4962.7 1706.83  4963.7 1706.33  5007.6 1706.83  5014.1 1710.68
  5021.1 1711.67  5035.2 1711.61  5042.4 1709.87  5049.4 1710.59  5056.5 1709.08
  5063.5 1712.43  5070.7 1711.72  5077.7 1713.28  5106.0 1711.31  5190.8 1719.77
  5558.7 1724.23  5898.0 1732.50  5975.9 1736.35  6025.3 1741.65  6202.2 1753.92
#Mann=3,-1,0
  4037.2    0.05       0  4962.7    0.03       0  5007.6    0.05       0
Bank Sta=4962.7,5007.6
Exp/Cntr=0.3,0.1

Type RM Length L Ch R = 1,38428,541,541,541
BEGIN DESCRIPTION:
Spring Creek 58.0
END DESCRIPTION:
XS GIS Cut Line= 3
      1635705.02      6898938.02      1636455.00      6899638.00
      1636954.97      6900287.96
#Sta/Elev= 30
  3974.1 1765.36  4016.3 1760.54  4037.8 1754.09  4087.2 1744.24  4115.5 1735.76
  4129.7 1728.53  4151.2 1721.54  4186.3 1716.30  4243.0 1714.52  4349.0 1714.21
  4561.5 1715.38  4625.0 1714.06  4688.5 1710.76  4724.2 1712.60  4794.8 1712.69
  4837.1 1711.00  4901.1 1712.03  4957.7 1710.69  4978.7 1706.29  4992.9 1705.72
  4996.6 1707.61  4999.3 1705.65  5000.3 1705.15  5044.2 1705.65  5050.5 1713.59
  5092.4 1717.76  5378.5 1720.23  5584.4 1725.18  5628.0 1725.10  5820.0 1737.90
#Mann=3,-1,0
  3974.1    0.05       0  4999.3    0.05       0  5044.2    0.05       0
Bank Sta=4999.3,5044.2
Exp/Cntr=0.3,0.1

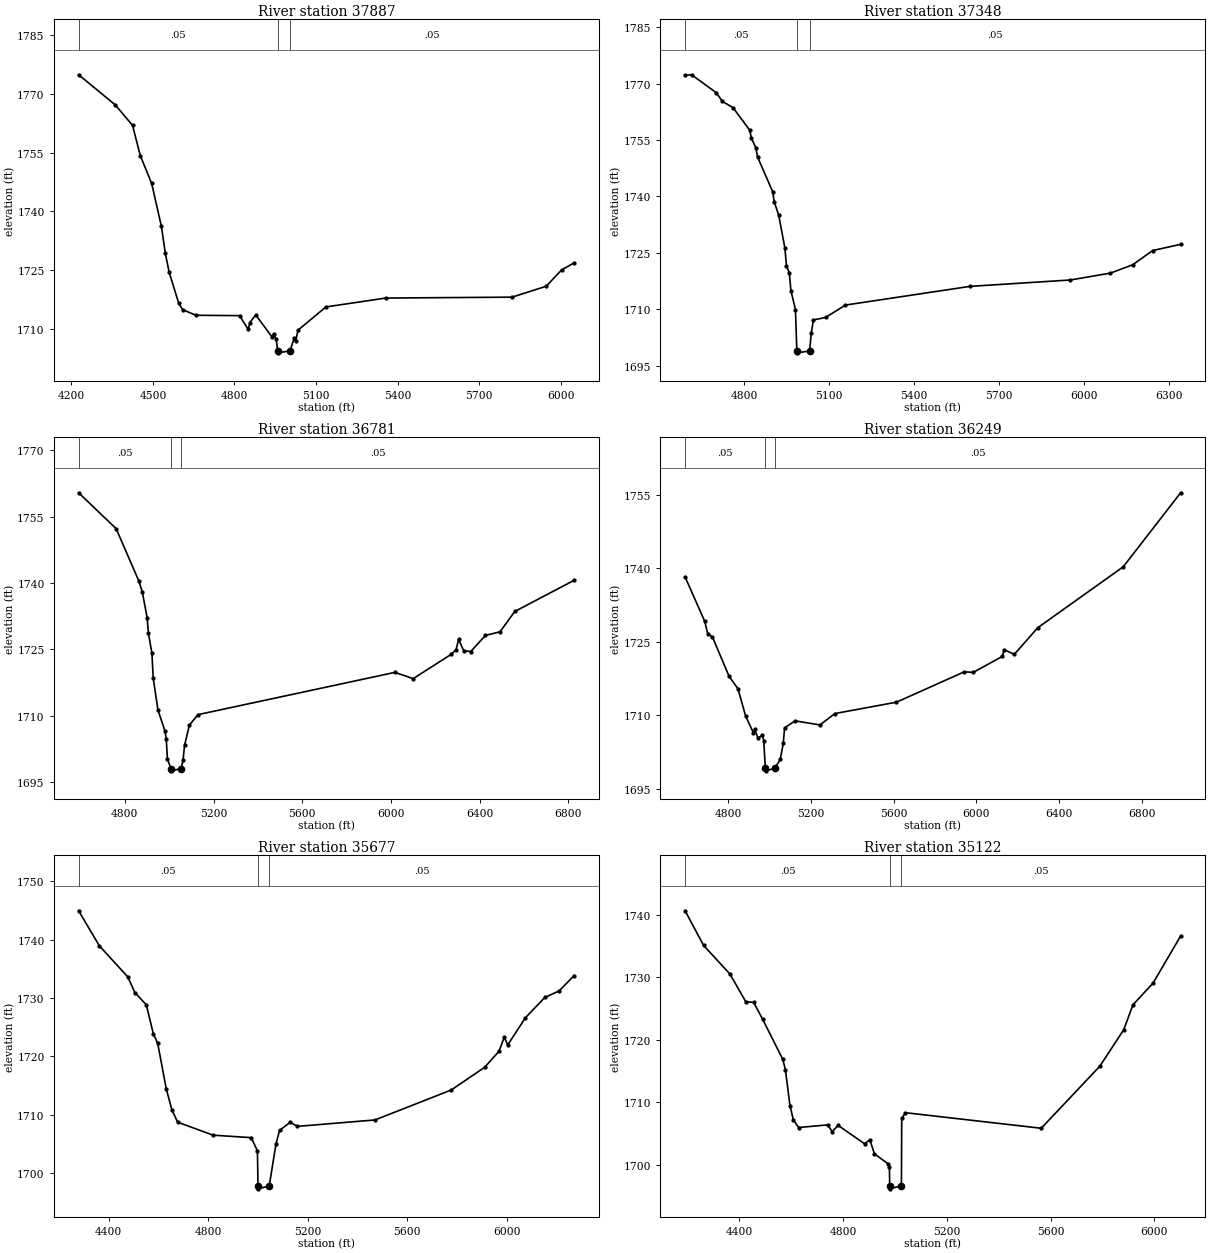
Type RM Length L Ch R = 1,37887,539,539,539
BEGIN DESCRIPTION:
Mapping XS 1655c9eb
END DESCRIPTION:
XS GIS Cut Line= 3
      1635492.12      6898961.41      1635835.90      6899260.05
      1636495.65      6900458.01
#Sta/Elev= 30
  4226.8 1774.87  4361.5 1767.19  4425.1 1761.95  4453.6 1754.25  4495.5 1747.11
  4531.4 1736.13  4545.7 1729.28  4559.9 1724.44  4595.0 1716.52  4609.3 1714.89
  4658.7 1713.46  4818.8 1713.37  4850.9 1709.84  4856.7 1711.60  4878.4 1713.55
  4938.1 1707.93  4943.8 1708.76  4953.8 1707.28  4959.2 1704.37  4960.2 1703.87
  5004.1 1704.37  5019.5 1707.55  5025.2 1706.82  5033.7 1709.65  5136.5 1715.59
  5356.6 1717.86  5821.5 1718.09  5947.0 1720.88  6004.1 1725.08  6049.8 1726.84
#Mann=3,-1,0
  4226.8    0.05       0  4959.2    0.03       0  5004.1    0.05       0
Bank Sta=4959.2,5004.1
Exp/Cntr=0.3,0.1

Type RM Length L Ch R = 1,37348,567,567,567
BEGIN DESCRIPTION:
Spring Creek 57.0
END DESCRIPTION:
XS GIS Cut Line= 3
      1635304.98      6899337.96      1635505.00      6899688.00
      1636516.44      6900576.00
#Sta/Elev= 30
  4592.4 1772.22  4615.5 1772.33  4702.6 1767.56  4724.2 1765.25  4761.6 1763.60
  4820.6 1757.59  4826.4 1755.50  4842.2 1752.92  4848.0 1750.53  4901.3 1741.30
  4907.0 1738.58  4922.9 1734.98  4944.5 1726.36  4950.2 1721.60  4960.3 1719.65
  4966.0 1714.92  4981.9 1709.95  4986.8 1698.94  4987.8 1698.44  5031.8 1698.94
  5037.8 1703.73  5045.4 1707.19  5088.1 1707.84  5158.3 1711.13  5597.6 1716.10
  5952.5 1717.80  6093.9 1719.63  6171.7 1721.82  6242.9 1725.63  6341.5 1727.27
#Mann=3,-1,0
  4592.4    0.05       0  4986.8    0.03       0  5031.8    0.05       0
Bank Sta=4986.8,5031.8
Exp/Cntr=0.3,0.1

Type RM Length L Ch R = 1,36781,532,532,532
BEGIN DESCRIPTION:
Spring Creek 56.0
END DESCRIPTION:
XS GIS Cut Line= 3
      1635105.02      6899838.04      1635305.00      6900188.00
      1636926.20      6901037.83
#Sta/Elev= 30
  4592.1 1760.40  4761.2 1752.29  4863.4 1740.47  4879.3 1737.95  4900.9 1732.16
  4906.6 1728.64  4922.5 1724.13  4928.2 1718.52  4949.8 1711.25  4981.5 1706.54
  4987.2 1704.67  4992.3 1700.20  5008.6 1698.06  5009.6 1697.56  5053.6 1698.06
  5062.9 1700.01  5069.6 1703.36  5091.6 1707.91  5130.1 1710.26  6017.6 1719.81
  6100.2 1718.40  6271.0 1723.88  6293.1 1724.94  6304.9 1727.25  6327.5 1724.73
  6359.3 1724.52  6425.5 1728.15  6491.6 1728.99  6557.8 1733.57  6825.6 1740.63
#Mann=3,-1,0
  4592.1    0.05       0  5008.6    0.05       0  5053.6    0.05       0
Bank Sta=5008.6,5053.6
Exp/Cntr=0.3,0.1

Type RM Length L Ch R = 1,36249,572,572,572
BEGIN DESCRIPTION:
Spring Creek 55.0
END DESCRIPTION:
XS GIS Cut Line= 3
      1634704.99      6900437.99      1635055.00      6900638.00
      1636605.03      6901888.02
#Sta/Elev= 30
  4592.3 1738.24  4686.6 1729.24  4702.5 1726.57  4724.0 1726.04  4804.7 1717.98
  4847.9 1715.42  4885.3 1709.78  4922.7 1706.41  4928.5 1707.12  4944.3 1705.38
  4965.9 1705.90  4972.4 1704.84  4980.0 1699.18  4981.0 1698.68  5025.2 1699.18
  5052.2 1701.01  5066.6 1704.28  5073.0 1707.45  5123.9 1708.88  5244.1 1708.05
  5316.1 1710.37  5613.6 1712.69  5941.5 1718.89  5984.6 1718.77  6125.9 1722.05
  6133.4 1723.41  6183.0 1722.45  6296.5 1727.89  6709.2 1740.31  6986.7 1755.42
#Mann=3,-1,0
  4592.3    0.05       0  4980.0    0.05       0  5025.2    0.05       0
Bank Sta=4980,5025.2
Exp/Cntr=0.3,0.1

Type RM Length L Ch R = 1,35677,555,555,555
BEGIN DESCRIPTION:
Spring Creek 54.0
END DESCRIPTION:
XS GIS Cut Line= 3
      1634554.99      6900487.97      1634855.00      6901138.00
      1635849.31      6901939.25
#Sta/Elev= 30
  4279.1 1744.93  4362.2 1738.94  4476.9 1733.60  4505.4 1730.91  4551.3 1728.83
  4579.7 1723.83  4597.2 1722.21  4631.6 1714.41  4654.1 1710.84  4677.0 1708.72
  4820.2 1706.49  4973.0 1706.07  4998.2 1703.80  5000.4 1697.80  5001.4 1697.30
  5045.6 1697.80  5072.6 1704.92  5087.0 1707.30  5130.2 1708.71  5159.0 1708.00
  5470.9 1709.10  5778.0 1714.24  5912.3 1718.13  5969.9 1720.88  5990.7 1723.26
  6005.1 1721.96  6075.5 1726.59  6153.9 1730.08  6211.4 1731.20  6272.0 1733.84
#Mann=3,-1,0
  4279.1    0.05       0  5000.4    0.05       0  5045.6    0.05       0
Bank Sta=5000.4,5045.6
Exp/Cntr=0.3,0.1

Type RM Length L Ch R = 1,35122,171,171,171
BEGIN DESCRIPTION:
Spring Creek 53.0
END DESCRIPTION:
XS GIS Cut Line= 3
      1634305.00      6900637.98      1634455.00      6901438.00
      1635204.97      6902237.97
#Sta/Elev= 30
  4191.1 1740.66  4262.3 1735.12  4364.1 1730.53  4425.1 1726.11  4455.6 1726.00
  4490.4 1723.28  4567.6 1716.90  4577.7 1715.27  4595.5 1709.48  4608.3 1707.24
  4628.6 1705.99  4740.5 1706.41  4758.3 1705.34  4781.2 1706.33  4883.0 1703.39
  4903.3 1704.02  4921.1 1701.78  4973.7 1700.18  4978.8 1699.60  4979.9 1696.68
  4980.9 1696.18  5025.1 1696.68  5026.3 1707.44  5040.5 1708.36  5564.1 1705.87
  5790.3 1715.81  5882.3 1721.64  5917.7 1725.61  5995.4 1729.10  6101.6 1736.62
#Mann=3,-1,0
  4191.1    0.05       0  4979.9    0.05       0  5025.1    0.05       0
Bank Sta=4979.9,5025.1
Exp/Cntr=0.3,0.1

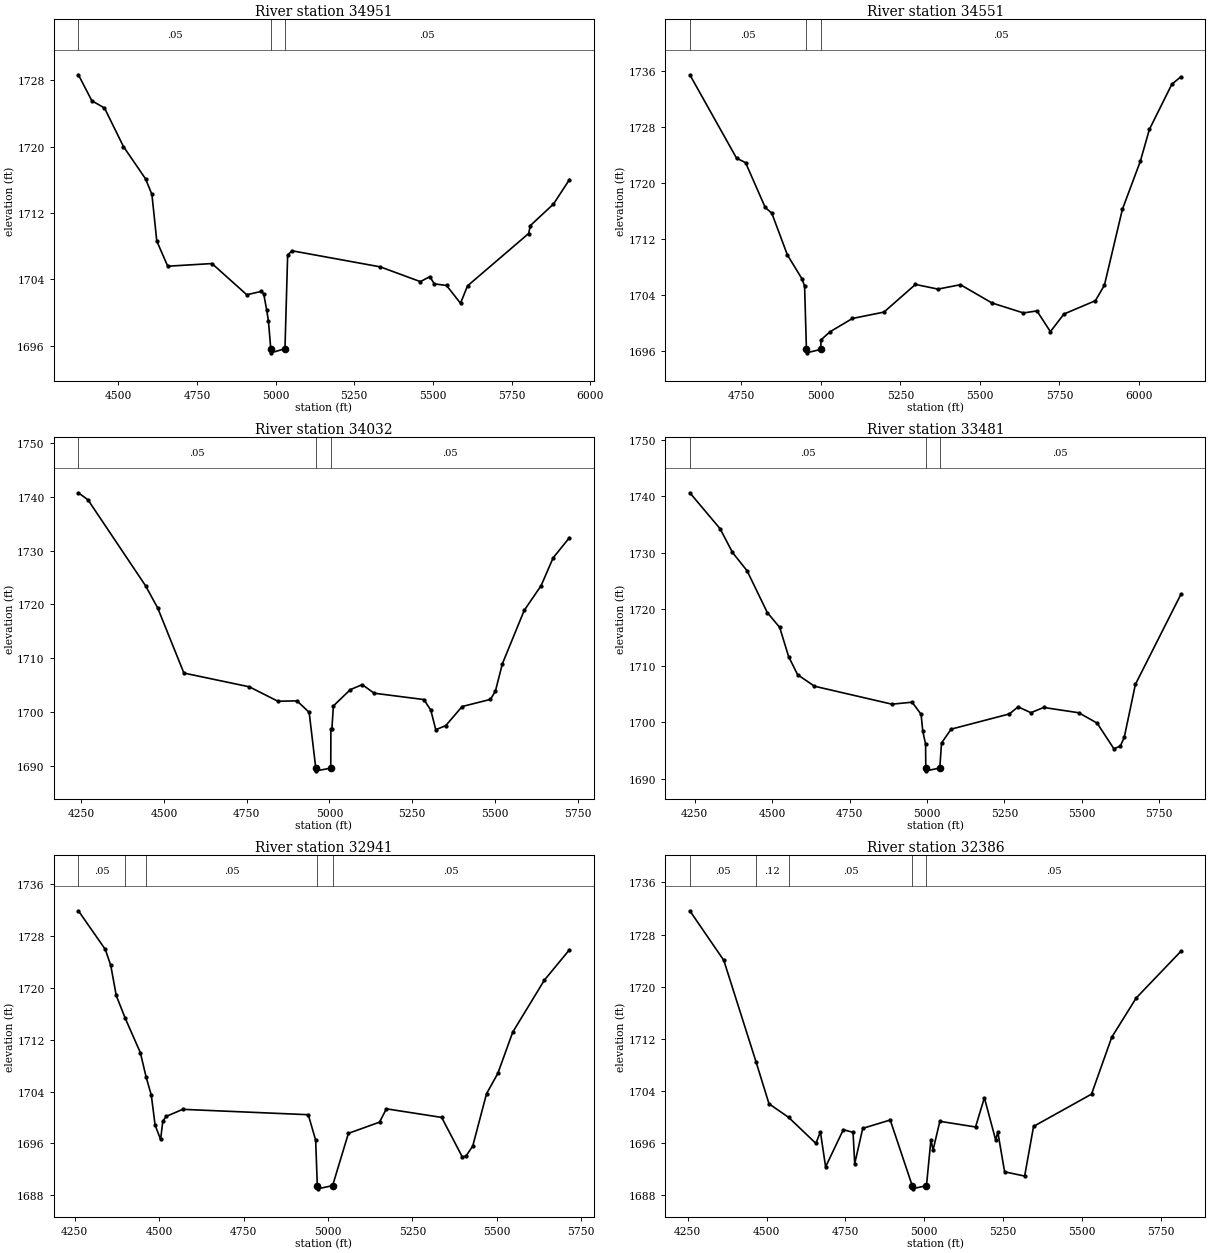
Type RM Length L Ch R = 1,34951,400,400,400
BEGIN DESCRIPTION:
Mapping XS c4b6bf86
END DESCRIPTION:
XS GIS Cut Line= 3
      1634264.23      6900805.55      1634321.52      6901357.64
      1633863.29      6902253.27
#Sta/Elev= 30
  4373.1 1728.67  4415.8 1725.54  4456.0 1724.67  4516.3 1720.02  4586.7 1716.12
  4606.8 1714.25  4622.3 1708.63  4657.1 1705.60  4797.8 1705.92  4908.4 1702.16
  4955.0 1702.57  4962.3 1702.25  4971.6 1700.34  4977.3 1698.96  4984.6 1695.66
  4985.6 1695.16  5029.8 1695.66  5038.3 1706.94  5052.1 1707.46  5332.9 1705.52
  5460.3 1703.74  5490.2 1704.34  5504.7 1703.47  5543.5 1703.28  5587.9 1701.13
  5610.1 1703.23  5804.4 1709.54  5810.0 1710.50  5883.4 1713.09  5934.2 1716.04
#Mann=3,-1,0
  4373.1    0.05       0  4984.6    0.05       0  5029.8    0.05       0
Bank Sta=4984.6,5029.8
Exp/Cntr=0.3,0.1

Type RM Length L Ch R = 1,34551,519,519,519
BEGIN DESCRIPTION:
Spring Creek 52.0
END DESCRIPTION:
XS GIS Cut Line= 3
      1634205.01      6900687.97      1634105.00      6901088.00
      1633305.01      6901887.99
#Sta/Elev= 30
  4588.2 1735.52  4735.1 1723.59  4763.5 1722.94  4825.3 1716.53  4845.9 1715.72
  4894.9 1709.74  4941.3 1706.28  4949.0 1705.26  4954.8 1696.23  4955.8 1695.73
  5000.0 1696.23  5000.5 1697.58  5028.8 1698.74  5099.5 1700.65  5198.5 1701.56
  5297.5 1705.52  5368.2 1704.85  5439.0 1705.48  5537.9 1702.87  5636.9 1701.44
  5679.4 1701.73  5721.8 1698.76  5764.2 1701.28  5863.2 1703.19  5891.5 1705.40
  5948.1 1716.27  6004.6 1723.16  6032.9 1727.70  6103.6 1734.17  6131.9 1735.23
#Mann=3,-1,0
  4588.2    0.05       0  4954.8    0.05       0  5000.0    0.05       0
Bank Sta=4954.8,5000
Exp/Cntr=0.3,0.1

Type RM Length L Ch R = 1,34032,551,551,551
BEGIN DESCRIPTION:
Spring Creek 51.0
END DESCRIPTION:
XS GIS Cut Line= 3
      1634055.00      6900538.00      1633655.00      6901188.00
      1633255.02      6901787.97
#Sta/Elev= 30
  4241.2 1740.77  4270.2 1739.45  4444.1 1723.47  4480.8 1719.34  4560.1 1707.21
  4757.8 1704.65  4844.1 1701.97  4902.0 1702.03  4938.7 1699.90  4958.7 1689.51
  4959.7 1689.01  5004.0 1689.51  5004.4 1696.75  5007.4 1696.75  5011.9 1701.09
  5063.0 1704.12  5099.1 1705.06  5135.1 1703.46  5285.4 1702.28  5306.4 1700.31
  5321.4 1696.67  5351.5 1697.42  5401.0 1700.98  5486.7 1702.31  5501.7 1703.85
  5522.7 1708.93  5588.8 1718.88  5639.9 1723.49  5676.0 1728.64  5725.5 1732.42
#Mann=3,-1,0
  4241.2    0.05       0  4958.7    0.05       0  5004.0    0.05       0
Bank Sta=4958.7,5004
Exp/Cntr=0.3,0.1

Type RM Length L Ch R = 1,33481,540,540,540
BEGIN DESCRIPTION:
Spring Creek 50.0
END DESCRIPTION:
XS GIS Cut Line= 3
      1634005.03      6900487.99      1633305.00      6900788.00
      1633105.01      6901587.97
#Sta/Elev= 30
  4233.9 1740.65  4331.8 1734.28  4371.7 1730.09  4418.9 1726.84  4484.2 1719.44
  4524.1 1716.83  4553.1 1711.65  4582.1 1708.45  4636.5 1706.41  4886.7 1703.23
  4952.0 1703.58  4981.0 1701.43  4986.4 1698.44  4995.5 1696.16  4996.1 1691.93
  4997.1 1691.43  5041.4 1691.93  5047.0 1696.36  5078.0 1698.81  5266.1 1701.50
  5294.4 1702.76  5335.7 1701.72  5376.9 1702.65  5490.3 1701.71  5549.6 1699.88
  5603.7 1695.34  5624.3 1695.79  5637.2 1697.35  5673.2 1706.73  5820.1 1722.66
#Mann=3,-1,0
  4233.9    0.05       0  4996.1    0.05       0  5041.4    0.05       0
Bank Sta=4996.1,5041.4
Exp/Cntr=0.3,0.1

Type RM Length L Ch R = 1,32941,555,555,555
BEGIN DESCRIPTION:
Spring Creek 49.0
END DESCRIPTION:
XS GIS Cut Line= 3
      1632504.99      6900287.97      1632855.00      6900938.00
      1633005.01      6901638.04
#Sta/Elev= 30
  4260.8 1731.93  4340.3 1725.97  4356.6 1723.50  4372.8 1718.85  4399.3 1715.35
  4444.2 1710.02  4461.6 1706.19  4476.6 1703.47  4488.0 1698.81  4504.2 1696.61
  4510.7 1699.39  4520.4 1700.16  4569.9 1701.26  4941.5 1700.43  4963.4 1696.50
  4968.3 1689.48  4969.3 1688.98  5013.6 1689.48  5060.4 1697.55  5152.5 1699.28
  5172.9 1701.34  5336.6 1700.01  5397.9 1693.89  5409.0 1694.07  5428.6 1695.59
  5469.5 1703.68  5502.8 1706.80  5547.1 1713.19  5640.8 1721.22  5715.0 1725.91
#Mann=5,-1,0
  4260.8    0.05       0  4399.3    0.12       0  4461.6    0.05       0
  4968.3    0.05       0  5013.6    0.05       0
Bank Sta=4968.3,5013.6
Exp/Cntr=0.3,0.1

Type RM Length L Ch R = 1,32386,565,565,565
BEGIN DESCRIPTION:
Spring Creek 48.0
END DESCRIPTION:
XS GIS Cut Line= 3
      1632105.01      6900388.02      1632355.00      6901088.00
      1632904.99      6901687.99
#Sta/Elev= 30
  4256.8 1731.64  4364.6 1724.03  4466.6 1708.49  4507.9 1702.03  4570.2 1699.94
  4656.6 1695.95  4670.9 1697.73  4687.4 1692.35  4743.6 1698.06  4774.4 1697.64
  4779.7 1692.84  4805.2 1698.26  4892.3 1699.54  4962.0 1689.48  4963.0 1688.98
  5007.3 1689.48  5021.4 1696.51  5028.1 1694.92  5049.7 1699.34  5162.9 1698.47
  5190.9 1702.95  5226.7 1696.48  5233.5 1697.68  5255.1 1691.59  5318.6 1690.94
  5346.9 1698.56  5530.7 1703.51  5594.8 1712.24  5672.5 1718.27  5814.0 1725.42
#Mann=5,-1,0
  4256.8    0.05       0  4466.6    0.12       0  4570.2    0.05       0
  4962.0    0.05       0  5007.3    0.05       0
Bank Sta=4962,5007.3
Exp/Cntr=0.3,0.1

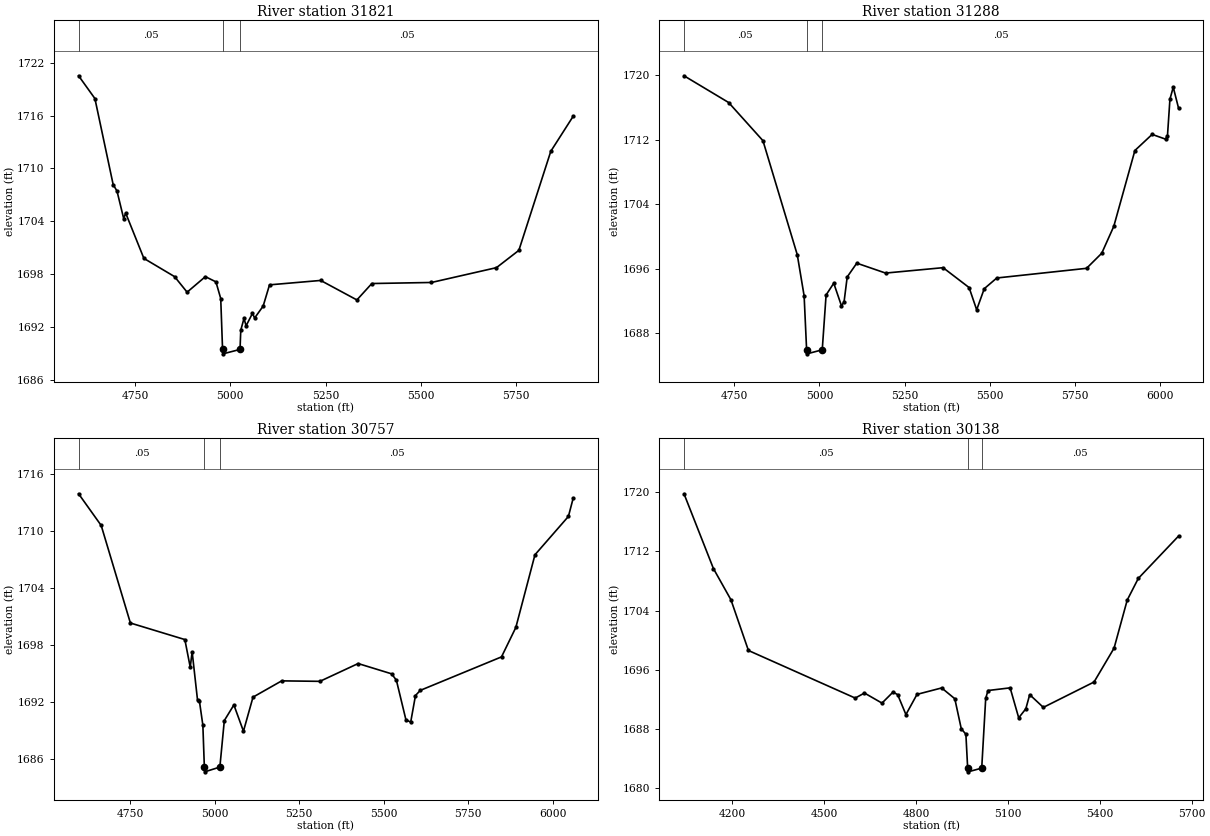
Type RM Length L Ch R = 1,31821,533,533,533
BEGIN DESCRIPTION:
Spring Creek 47.0
END DESCRIPTION:
XS GIS Cut Line= 3
      1631855.00      6900638.00      1631805.00      6901038.00
      1632204.98      6901837.96
#Sta/Elev= 30
  4602.1 1720.51  4644.9 1717.93  4692.8 1708.18  4702.9 1707.44  4720.5 1704.31
  4725.6 1704.95  4773.4 1699.81  4854.0 1697.74  4886.8 1695.98  4934.7 1697.74
  4962.4 1697.15  4975.0 1695.26  4979.8 1689.49  4980.8 1688.99  5025.6 1689.49
  5027.6 1691.67  5036.0 1693.00  5041.6 1692.17  5058.3 1693.58  5063.9 1693.05
  5086.3 1694.40  5103.0 1696.81  5237.2 1697.31  5332.2 1695.10  5371.4 1696.96
  5527.9 1697.08  5698.4 1698.76  5757.1 1700.72  5840.9 1711.95  5899.6 1715.92
#Mann=3,-1,0
  4602.1    0.05       0  4979.8    0.05       0  5025.6    0.05       0
Bank Sta=4979.8,5025.6
Exp/Cntr=0.3,0.1

Type RM Length L Ch R = 1,31288,531,531,531
BEGIN DESCRIPTION:
Spring Creek 46.0
END DESCRIPTION:
XS GIS Cut Line= 3
      1631305.00      6900688.00      1631355.00      6901088.00
      1631815.05      6902030.84
#Sta/Elev= 30
  4602.3 1719.95  4733.3 1716.63  4834.1 1711.89  4934.9 1697.72  4955.0 1692.62
  4962.3 1685.92  4963.3 1685.42  5008.2 1685.92  5019.5 1692.73  5042.0 1694.19
  5064.5 1691.40  5072.2 1691.85  5081.5 1694.97  5109.6 1696.68  5194.1 1695.45
  5363.0 1696.12  5439.4 1693.65  5461.6 1690.89  5483.9 1693.51  5520.7 1694.84
  5784.3 1696.04  5828.8 1697.91  5864.2 1701.25  5926.2 1710.67  5976.8 1712.67
  6016.3 1712.08  6021.9 1712.53  6029.1 1717.05  6038.8 1718.53  6054.5 1715.91
#Mann=3,-1,0
  4602.3    0.05       0  4962.3    0.05       0  5008.2    0.05       0
Bank Sta=4962.3,5008.2
Exp/Cntr=0.3,0.1

Type RM Length L Ch R = 1,30757,619,619,619
BEGIN DESCRIPTION:
Spring Creek 45.0
END DESCRIPTION:
XS GIS Cut Line= 3
      1630605.04      6901088.02      1630955.00      6901288.00
      1631704.98      6902037.98
#Sta/Elev= 30
  4597.4 1713.91  4664.3 1710.58  4750.7 1700.33  4911.9 1698.59  4927.8 1695.69
  4933.5 1697.30  4949.4 1692.23  4955.1 1692.10  4965.2 1689.59  4969.6 1685.19
  4970.6 1684.69  5015.5 1685.19  5028.7 1690.08  5057.0 1691.72  5085.3 1688.96
  5113.6 1692.54  5198.5 1694.25  5311.6 1694.20  5424.7 1696.07  5523.7 1694.99
  5537.9 1694.32  5566.2 1690.15  5580.3 1689.92  5594.4 1692.71  5608.6 1693.25
  5849.0 1696.77  5891.4 1699.86  5948.0 1707.50  6047.0 1711.53  6061.1 1713.44
#Mann=3,-1,0
  4597.4    0.05       0  4969.6    0.05       0  5015.5    0.05       0
Bank Sta=4969.6,5015.5
Exp/Cntr=0.3,0.1

Type RM Length L Ch R = 1,30138,525,525,525
BEGIN DESCRIPTION:
Mapping XS 20af5416
END DESCRIPTION:
XS GIS Cut Line= 3
      1630221.29      6901235.71      1630523.40      6901593.38
      1631480.88      6902224.76
#Sta/Elev= 30
  4042.3 1719.78  4138.4 1709.67  4195.6 1705.45  4252.7 1698.60  4601.4 1692.17
  4631.6 1692.85  4688.8 1691.49  4724.9 1692.98  4740.0 1692.63  4767.0 1689.94
  4803.2 1692.67  4883.7 1693.54  4926.6 1692.08  4947.7 1688.03  4962.8 1687.28
  4968.6 1682.70  4969.6 1682.20  5014.5 1682.70  5027.5 1692.12  5035.0 1693.19
  5107.3 1693.55  5135.3 1689.50  5158.5 1690.72  5171.2 1692.63  5215.7 1690.91
  5381.3 1694.34  5446.7 1698.92  5489.7 1705.42  5525.8 1708.34  5657.4 1714.07
#Mann=3,-1,0
  4042.3    0.05       0  4968.6    0.05       0  5014.5    0.05       0
Bank Sta=4968.6,5014.5
Exp/Cntr=0.3,0.1