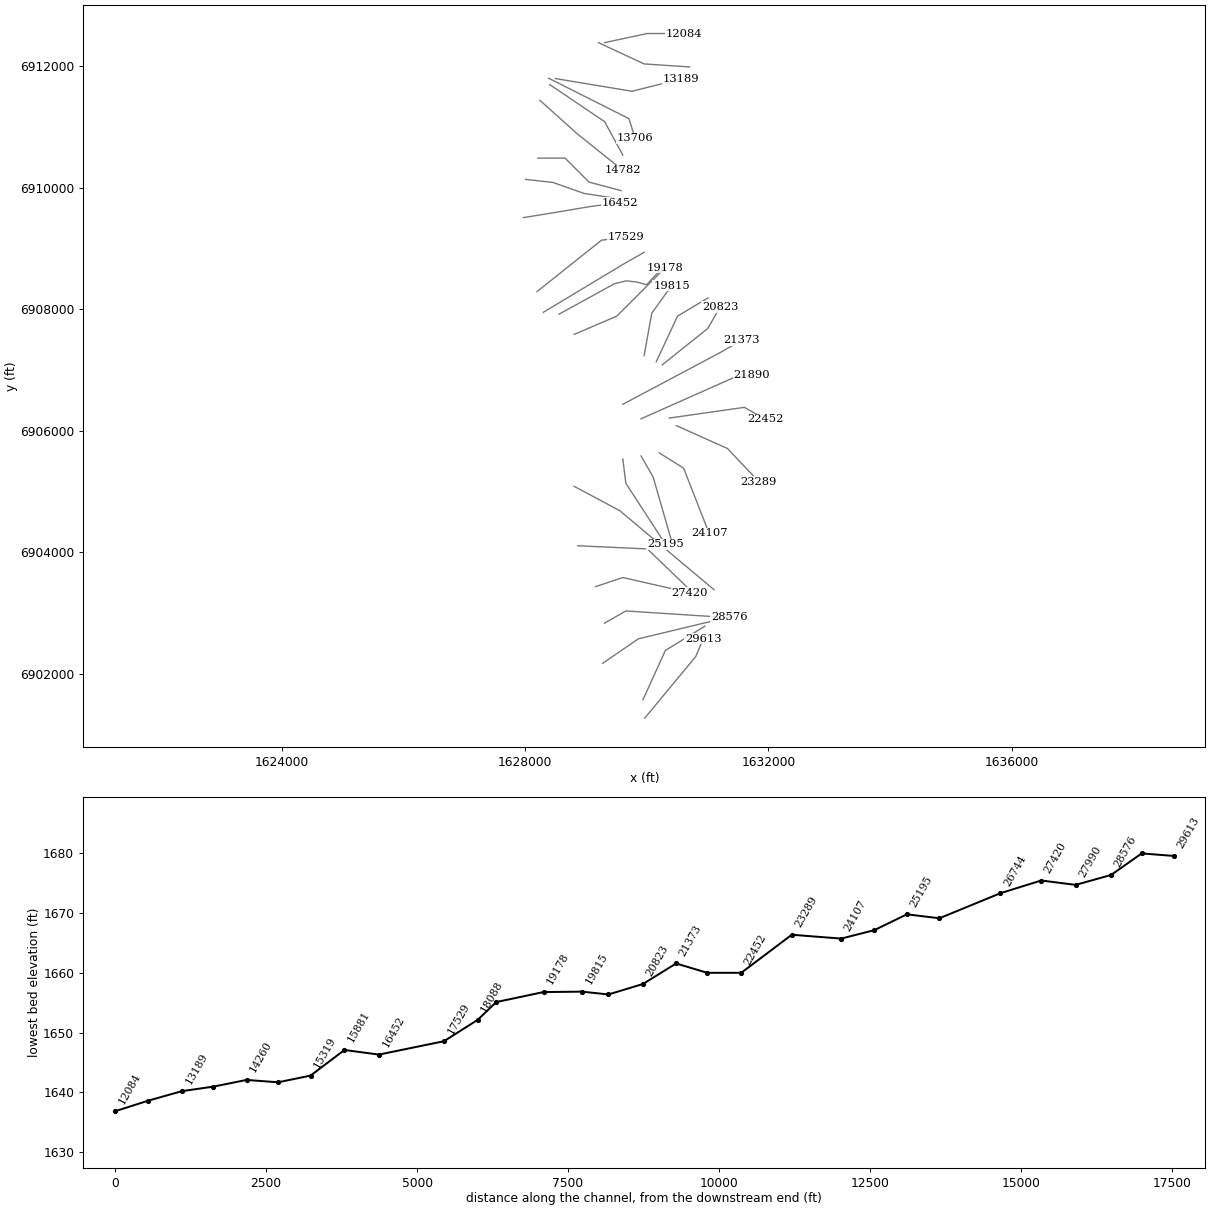
HEC-RAS study Spring Creek.prj: Spring Creek Base Level Engineering

--- Spring Creek.g01 (geometry) --- (continued)

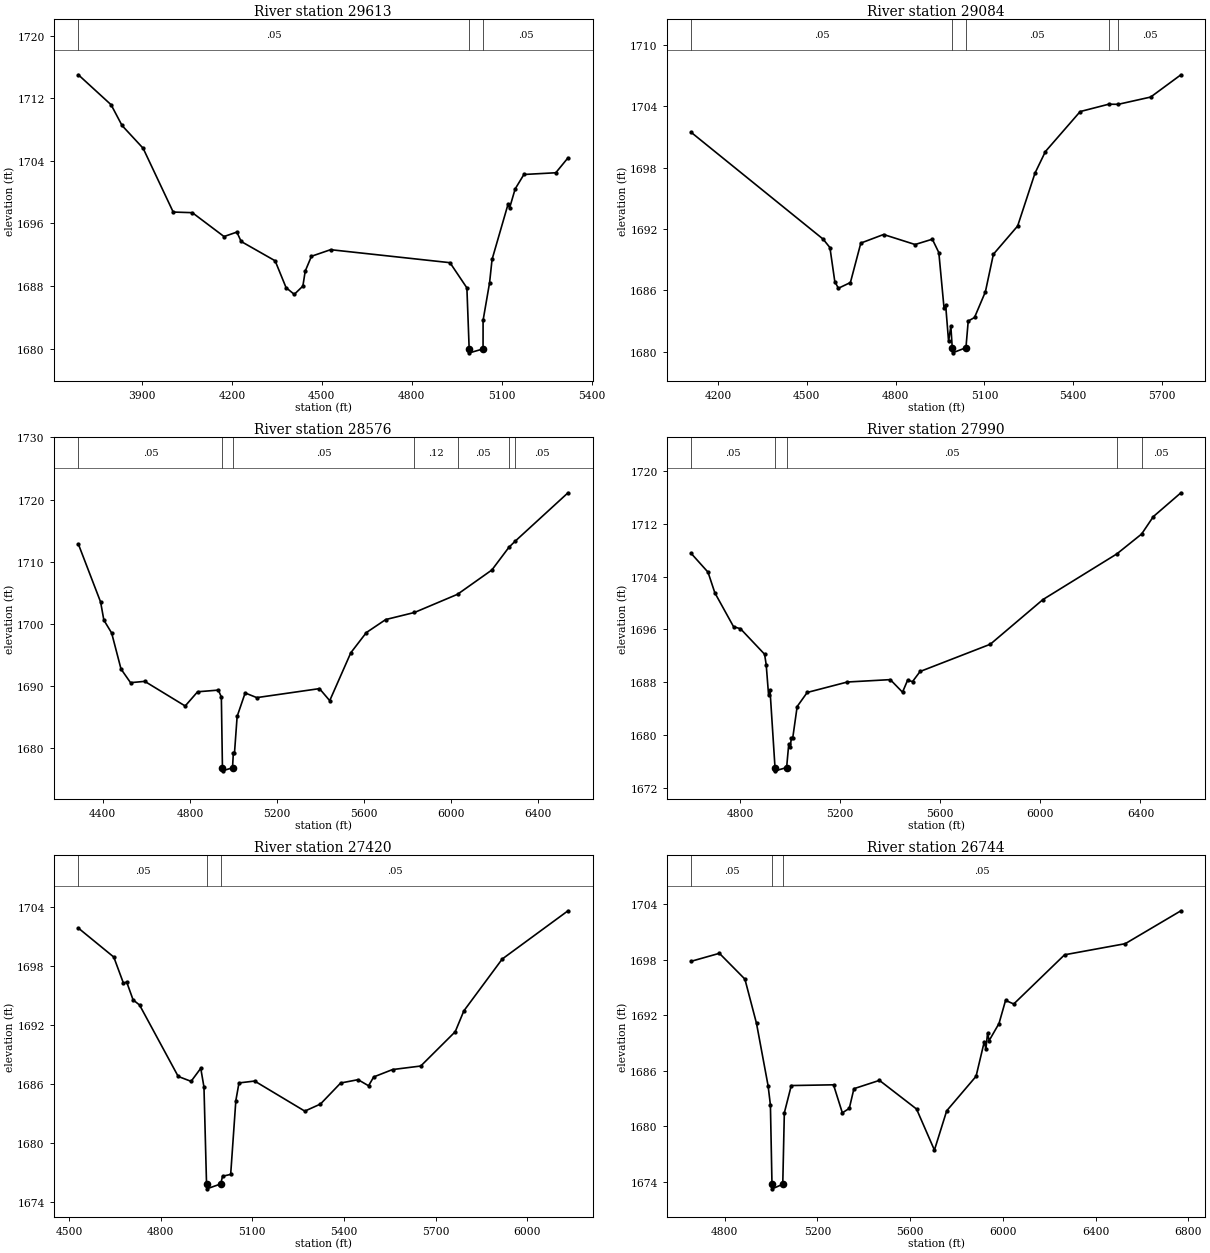
Type RM Length L Ch R = 1,29613,529,529,529
BEGIN DESCRIPTION:
Spring Creek 44.0
END DESCRIPTION:
XS GIS Cut Line= 3
      1629964.40      6901273.97      1630805.00      6902288.00
      1630926.17      6902579.48
#Sta/Elev= 30
  3688.2 1714.99  3797.4 1711.16  3833.9 1708.51  3904.2 1705.60  4004.5 1697.45
  4068.3 1697.37  4174.0 1694.32  4216.8 1694.89  4231.1 1693.69  4344.4 1691.22
  4380.9 1687.79  4408.2 1686.93  4436.9 1687.99  4444.7 1689.90  4465.5 1691.80
  4529.3 1692.64  4927.4 1690.98  4983.8 1687.76  4991.4 1679.96  4992.4 1679.46
  5037.7 1679.96  5037.8 1683.61  5059.5 1688.43  5067.7 1691.39  5120.8 1698.42
  5126.2 1697.97  5144.7 1700.40  5173.9 1702.25  5280.2 1702.47  5321.0 1704.38
#Mann=3,-1,0
  3688.2    0.05       0  4991.4    0.05       0  5037.7    0.05       0
Bank Sta=4991.4,5037.7
Exp/Cntr=0.3,0.1

Type RM Length L Ch R = 1,29084,508,508,508
BEGIN DESCRIPTION:
Spring Creek 43.0
END DESCRIPTION:
XS GIS Cut Line= 3
      1629936.10      6901576.38      1630305.00      6902388.00
      1630954.97      6902787.98
#Sta/Elev= 30
  4109.3 1701.45  4554.8 1691.01  4577.9 1690.18  4594.4 1686.85  4606.5 1686.20
  4647.1 1686.76  4682.3 1690.62  4759.2 1691.46  4865.7 1690.48  4923.9 1691.00
  4945.9 1689.69  4963.5 1684.26  4969.0 1684.54  4978.9 1681.00  4986.5 1682.50
  4991.2 1680.38  4992.2 1679.88  5037.5 1680.38  5045.2 1682.99  5066.5 1683.34
  5103.2 1685.85  5130.3 1689.53  5212.2 1692.29  5270.9 1697.47  5306.1 1699.58
  5423.5 1703.49  5520.0 1704.21  5552.1 1704.20  5661.7 1704.91  5764.0 1707.09
#Mann=5,-1,0
  4109.3    0.05       0  4991.2    0.05       0  5037.5    0.05       0
  5520.0    0.12       0  5552.1    0.05       0
Bank Sta=4991.2,5037.5
Exp/Cntr=0.3,0.1

Type RM Length L Ch R = 1,28576,586,586,586
BEGIN DESCRIPTION:
Spring Creek 42.0
END DESCRIPTION:
XS GIS Cut Line= 3
      1629273.40      6902176.71      1629860.74      6902579.70
      1631354.99      6902938.00
#Sta/Elev= 30
  4287.7 1712.83  4390.0 1703.48  4404.9 1700.57  4440.7 1698.49  4483.7 1692.69
  4527.4 1690.49  4592.8 1690.70  4778.4 1686.73  4835.4 1689.02  4930.7 1689.29
  4944.5 1688.18  4949.5 1676.78  4950.5 1676.28  4995.8 1676.78  4999.5 1679.14
  5004.8 1679.14  5017.0 1685.05  5053.8 1688.83  5107.2 1688.08  5395.1 1689.53
  5442.2 1687.59  5539.1 1695.31  5610.3 1698.56  5699.4 1700.66  5831.4 1701.80
  6029.1 1704.73  6187.0 1708.65  6265.3 1712.31  6294.3 1713.30  6536.6 1721.09
#Mann=7,-1,0
  4287.7    0.05       0  4949.5    0.05       0  4995.8    0.05       0
  5831.4    0.12       0  6029.1    0.05       0  6265.3    0.12       0
  6294.3    0.05       0
Bank Sta=4949.5,4995.8
Exp/Cntr=0.3,0.1

Type RM Length L Ch R = 1,27990,570,570,570
BEGIN DESCRIPTION:
Spring Creek 41.0
END DESCRIPTION:
XS GIS Cut Line= 3
      1629305.01      6902838.00      1629655.00      6903038.00
      1631204.97      6902938.00
#Sta/Elev= 30
  4605.4 1707.49  4672.3 1704.67  4699.7 1701.54  4774.6 1696.41  4801.9 1696.12
  4898.4 1692.26  4904.8 1690.69  4914.2 1686.15  4920.0 1686.88  4940.0 1675.13
  4941.0 1674.63  4986.4 1675.13  4994.8 1678.63  5000.6 1678.20  5005.6 1679.64
  5011.0 1679.64  5028.5 1684.35  5068.6 1686.48  5229.0 1688.06  5400.6 1688.42
  5449.4 1686.52  5469.5 1688.31  5489.5 1688.13  5519.6 1689.65  5800.1 1693.77
  6010.6 1700.53  6305.3 1707.42  6404.5 1710.43  6451.5 1713.07  6561.7 1716.67
#Mann=5,-1,0
  4605.4    0.05       0  4940.0    0.05       0  4986.4    0.05       0
  6305.3    0.12       0  6404.5    0.05       0
Bank Sta=4940,4986.4
Exp/Cntr=0.3,0.1

Type RM Length L Ch R = 1,27420,676,676,676
BEGIN DESCRIPTION:
Spring Creek 40.0
END DESCRIPTION:
XS GIS Cut Line= 3
      1629154.95      6903437.98      1629605.00      6903588.00
      1630704.96      6903338.01
#Sta/Elev= 30
  4530.5 1701.90  4646.5 1698.95  4678.1 1696.29  4688.7 1696.41  4709.7 1694.59
  4730.8 1694.07  4857.3 1686.80  4899.5 1686.30  4931.1 1687.63  4941.6 1685.72
  4950.0 1675.86  4951.0 1675.36  4996.5 1675.86  5002.3 1676.64  5029.0 1676.83
  5045.9 1684.34  5056.2 1686.14  5107.4 1686.33  5271.5 1683.27  5322.8 1683.99
  5388.9 1686.13  5445.9 1686.47  5480.2 1685.85  5497.1 1686.75  5558.7 1687.50
  5651.0 1687.86  5763.8 1691.35  5792.0 1693.47  5917.6 1698.75  6132.9 1703.66
#Mann=3,-1,0
  4530.5    0.05       0  4950.0    0.03       0  4996.5    0.05       0
Bank Sta=4950,4996.5
Exp/Cntr=0.3,0.1

Type RM Length L Ch R = 1,26744,1011,1011,1011
BEGIN DESCRIPTION:
Spring Creek 39.0
END DESCRIPTION:
XS GIS Cut Line= 3
      1628863.71      6904110.74      1630009.51      6904058.66
      1630705.03      6903387.97
#Sta/Elev= 30
  4655.3 1697.85  4776.7 1698.71  4886.8 1695.92  4936.9 1691.13  4986.9 1684.39
  4996.9 1682.31  5003.7 1673.74  5004.7 1673.24  5050.2 1673.74  5057.0 1681.46
  5087.0 1684.41  5269.2 1684.49  5307.3 1681.46  5337.3 1681.94  5357.3 1684.07
  5467.4 1684.97  5627.6 1681.87  5704.7 1677.43  5757.7 1681.68  5884.4 1685.41
  5919.9 1689.16  5926.8 1688.35  5934.0 1690.07  5941.0 1689.28  5983.4 1691.12
  6011.7 1693.62  6047.0 1693.23  6266.4 1698.55  6528.1 1699.75  6768.5 1703.31
#Mann=3,-1,0
  4655.3    0.05       0  5003.7    0.03       0  5050.2    0.05       0
Bank Sta=5003.7,5050.2
Exp/Cntr=0.3,0.1

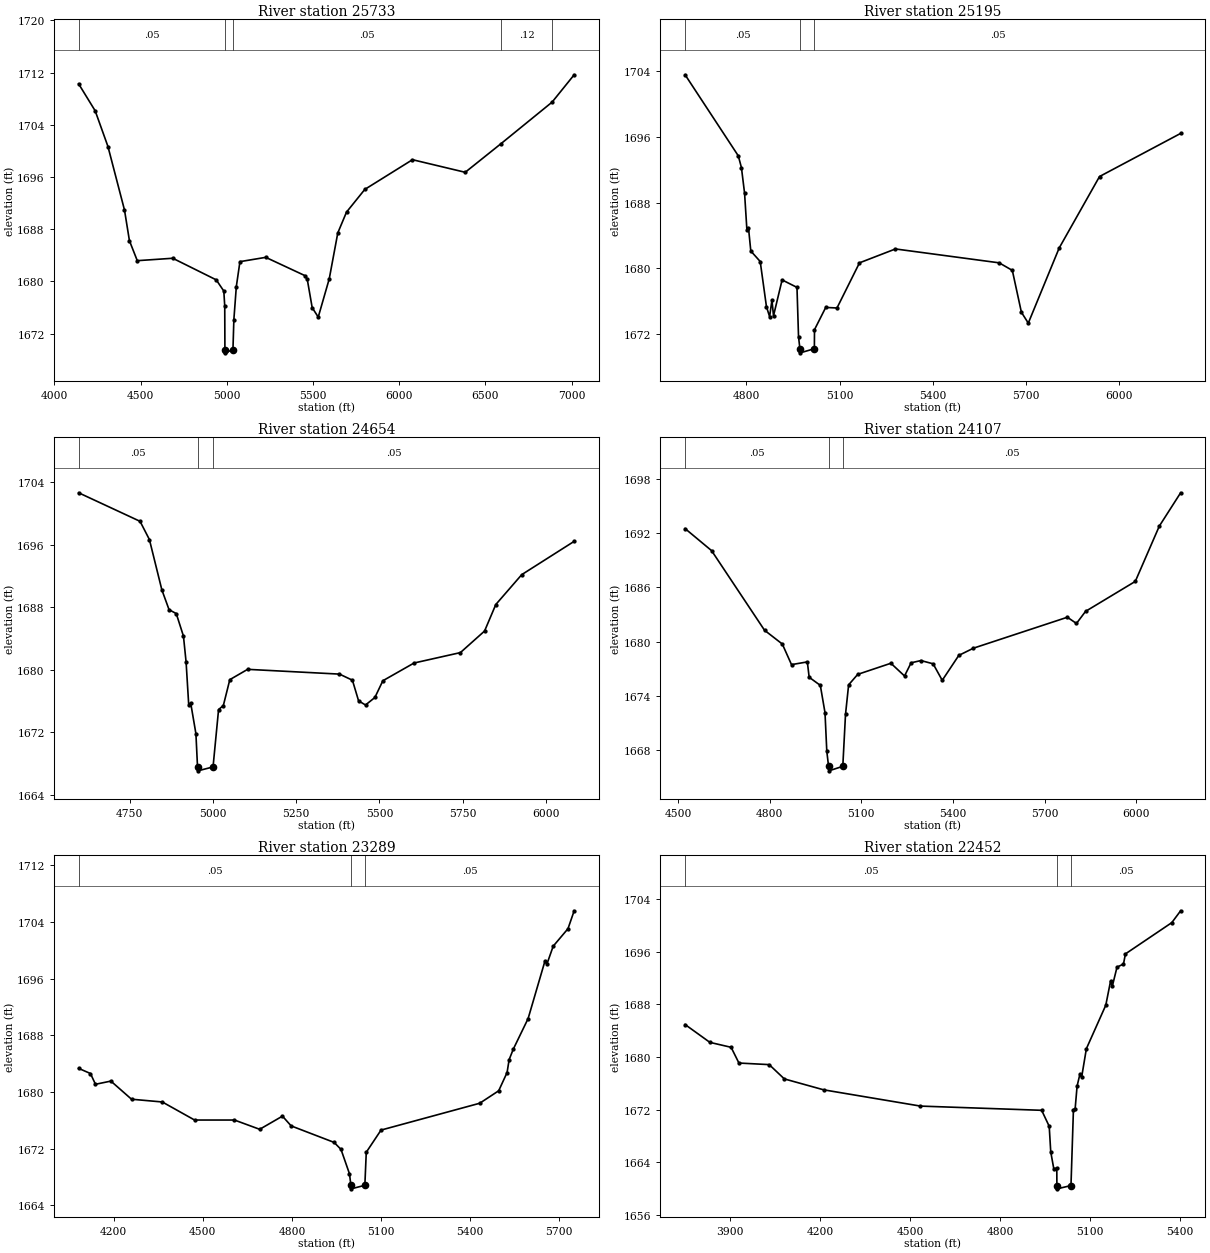
Type RM Length L Ch R = 1,25733,538,538,538
BEGIN DESCRIPTION:
Spring Creek 38.0
END DESCRIPTION:
XS GIS Cut Line= 3
      1628805.03      6905087.98      1629555.00      6904688.00
      1631105.03      6903387.97
#Sta/Elev= 30
  4141.3 1710.27  4237.2 1706.14  4311.3 1700.67  4407.2 1690.94  4435.9 1686.23
  4481.3 1683.18  4687.0 1683.55  4939.2 1680.24  4983.1 1678.52  4988.4 1676.20
  4989.4 1669.56  4990.4 1669.06  5036.0 1669.56  5041.3 1674.15  5055.6 1679.22
  5076.5 1683.03  5226.1 1683.69  5452.5 1680.90  5466.8 1680.33  5495.4 1675.98
  5530.5 1674.54  5594.3 1680.40  5643.8 1687.43  5694.4 1690.62  5800.5 1694.10
  6076.9 1698.65  6382.6 1696.72  6590.8 1701.12  6886.3 1707.47  7014.3 1711.66
#Mann=5,-1,0
  4141.3    0.05       0  4989.4    0.03       0  5036.0    0.05       0
  6590.8    0.12       0  6886.3    0.05       0
Bank Sta=4989.4,5036
Exp/Cntr=0.3,0.1

Type RM Length L Ch R = 1,25195,541,541,541
BEGIN DESCRIPTION:
Spring Creek 37.0
END DESCRIPTION:
XS GIS Cut Line= 3
      1629605.00      6905538.01      1629655.00      6905138.00
      1630305.00      6904138.01
#Sta/Elev= 30
  4602.7 1703.58  4774.0 1693.71  4784.1 1692.28  4794.2 1689.17  4801.7 1684.71
  4806.8 1684.96  4814.3 1682.12  4844.6 1680.84  4864.7 1675.34  4874.8 1674.13
  4882.4 1676.12  4887.4 1674.23  4915.1 1678.60  4963.0 1677.69  4968.0 1671.67
  4972.4 1670.22  4973.4 1669.72  5019.0 1670.22  5019.4 1672.54  5055.6 1675.25
  5091.8 1675.18  5164.3 1680.68  5280.1 1682.37  5614.1 1680.68  5656.5 1679.76
  5685.7 1674.66  5707.9 1673.34  5807.4 1682.49  5937.3 1691.19  6198.5 1696.44
#Mann=3,-1,0
  4602.7    0.05       0  4972.4    0.03       0  5019.0    0.05       0
Bank Sta=4972.4,5019
Exp/Cntr=0.3,0.1

Type RM Length L Ch R = 1,24654,547,547,547
BEGIN DESCRIPTION:
Spring Creek 36.0
END DESCRIPTION:
XS GIS Cut Line= 3
      1629904.99      6905588.01      1630105.00      6905238.00
      1630404.84      6904196.22
#Sta/Elev= 30
  4597.1 1702.63  4781.4 1698.98  4809.5 1696.65  4846.9 1690.21  4868.5 1687.68
  4890.1 1687.18  4911.7 1684.30  4919.6 1680.99  4927.5 1675.50  4933.3 1675.77
  4949.1 1671.82  4953.9 1667.57  4954.9 1667.07  5000.5 1667.57  5017.1 1674.91
  5031.4 1675.42  5050.8 1678.73  5104.3 1680.05  5380.0 1679.44  5418.8 1678.66
  5437.3 1676.02  5458.1 1675.49  5486.2 1676.45  5510.1 1678.59  5603.8 1680.86
  5742.8 1682.19  5815.4 1684.95  5849.1 1688.34  5926.9 1692.16  6084.3 1696.42
#Mann=3,-1,0
  4597.1    0.05       0  4953.9    0.03       0  5000.5    0.05       0
Bank Sta=4953.9,5000.5
Exp/Cntr=0.3,0.1

Type RM Length L Ch R = 1,24107,818,818,818
BEGIN DESCRIPTION:
Spring Creek 35.0
END DESCRIPTION:
XS GIS Cut Line= 3
      1630204.96      6905638.02      1630605.00      6905388.00
      1631024.65      6904315.96
#Sta/Elev= 30
  4522.7 1692.51  4609.4 1690.07  4782.8 1681.25  4841.1 1679.72  4871.2 1677.44
  4923.1 1677.74  4929.0 1676.04  4965.6 1675.14  4980.9 1672.12  4986.8 1667.84
  4992.6 1666.17  4993.6 1665.67  5039.2 1666.17  5048.1 1671.93  5058.3 1675.20
  5088.1 1676.36  5196.7 1677.59  5241.4 1676.18  5262.9 1677.64  5295.1 1677.89
  5335.0 1677.53  5364.9 1675.70  5419.1 1678.46  5467.0 1679.26  5774.7 1682.69
  5804.5 1682.00  5834.3 1683.34  5997.2 1686.66  6075.9 1692.79  6145.7 1696.48
#Mann=3,-1,0
  4522.7    0.05       0  4992.6    0.03       0  5039.2    0.05       0
Bank Sta=4992.6,5039.2
Exp/Cntr=0.3,0.1

Type RM Length L Ch R = 1,23289,837,837,837
BEGIN DESCRIPTION:
Mapping XS 5e519a80
END DESCRIPTION:
XS GIS Cut Line= 3
      1630488.72      6906086.42      1631325.49      6905711.44
      1631842.85      6905166.30
#Sta/Elev= 30
  4081.7 1683.33  4121.5 1682.60  4138.4 1681.08  4190.3 1681.53  4259.8 1678.97
  4363.5 1678.58  4472.1 1676.03  4606.3 1676.03  4691.3 1674.72  4768.0 1676.58
  4797.3 1675.20  4941.9 1672.87  4965.1 1671.88  4993.7 1668.43  4998.4 1666.81
  4999.4 1666.31  5045.4 1666.81  5050.2 1671.48  5099.9 1674.61  5432.1 1678.40
  5496.0 1680.16  5524.3 1682.74  5531.2 1684.56  5545.3 1686.05  5595.1 1690.36
  5651.4 1698.43  5658.6 1698.08  5679.6 1700.59  5729.4 1703.06  5750.2 1705.59
#Mann=3,-1,0
  4081.7    0.05       0  4998.4    0.03       0  5045.4    0.05       0
Bank Sta=4998.4,5045.4
Exp/Cntr=0.3,0.1

Type RM Length L Ch R = 1,22452,562,562,562
BEGIN DESCRIPTION:
Spring Creek 34.0
END DESCRIPTION:
XS GIS Cut Line= 3
      1630367.20      6906211.44      1631605.00      6906388.00
      1631954.96      6906188.02
#Sta/Elev= 30
  3749.2 1684.92  3831.9 1682.21  3902.7 1681.46  3928.8 1679.07  4029.8 1678.83
  4080.3 1676.66  4211.6 1675.00  4534.5 1672.53  4938.9 1671.89  4964.1 1669.46
  4969.2 1665.57  4979.3 1663.03  4989.4 1663.09  4989.7 1660.46  4990.7 1659.96
  5036.7 1660.46  5044.9 1671.98  5050.6 1672.11  5057.1 1675.56  5066.5 1677.38
  5072.2 1676.90  5088.1 1681.25  5152.9 1687.86  5168.7 1691.50  5174.5 1690.71
  5190.3 1693.64  5211.9 1694.11  5218.4 1695.65  5373.1 1700.40  5402.6 1702.20
#Mann=3,-1,0
  3749.2    0.05       0  4989.7    0.05       0  5036.7    0.05       0
Bank Sta=4989.7,5036.7
Exp/Cntr=0.3,0.1

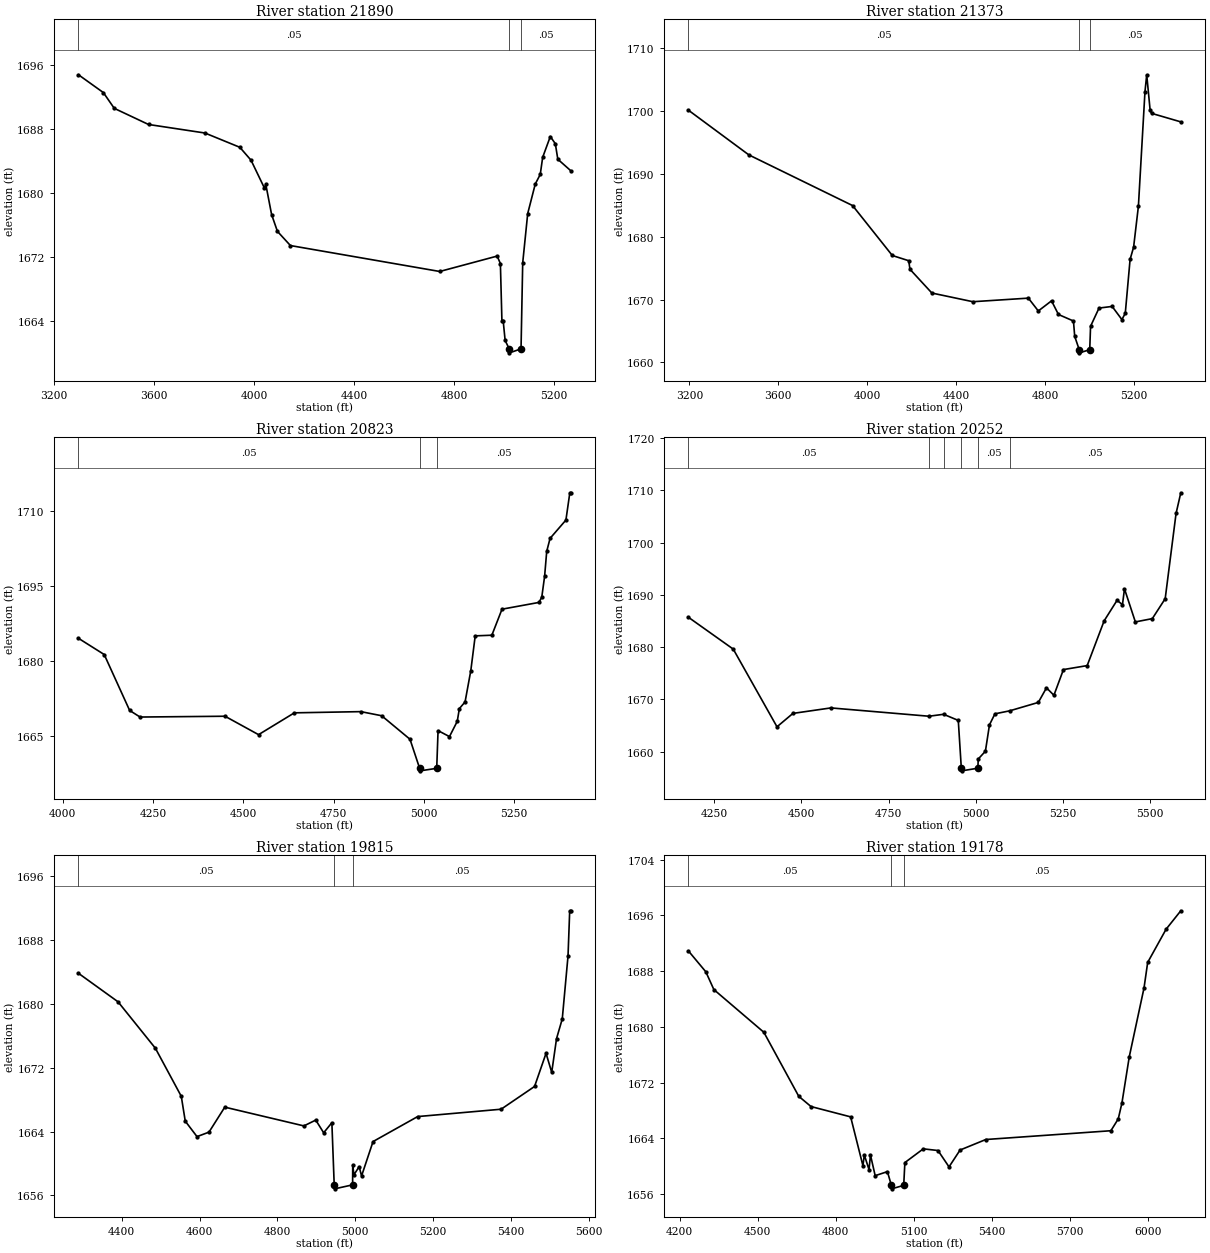
Type RM Length L Ch R = 1,21890,517,517,517
BEGIN DESCRIPTION:
Spring Creek 33.0
END DESCRIPTION:
XS GIS Cut Line= 3
      1629904.02      6906199.27      1631455.00      6906888.00
      1631726.95      6906912.83
#Sta/Elev= 30
  3297.6 1694.82  3397.1 1692.59  3440.9 1690.61  3577.8 1688.59  3803.5 1687.52
  3943.1 1685.73  3988.0 1684.11  4041.6 1680.62  4047.1 1681.08  4070.3 1677.30
  4093.6 1675.19  4145.6 1673.41  4743.0 1670.16  4972.7 1672.09  4985.7 1671.16
  4991.9 1663.90  4997.1 1663.90  5004.7 1661.51  5021.1 1660.46  5022.1 1659.96
  5068.3 1660.46  5075.0 1671.24  5095.0 1677.42  5125.2 1681.12  5145.2 1682.33
  5154.9 1684.47  5185.4 1687.08  5205.5 1686.18  5215.5 1684.23  5267.7 1682.78
#Mann=3,-1,0
  3297.6    0.05       0  5021.1    0.03       0  5068.3    0.05       0
Bank Sta=5021.1,5068.3
Exp/Cntr=0.3,0.1

Type RM Length L Ch R = 1,21373,550,550,550
BEGIN DESCRIPTION:
Spring Creek 32.0
END DESCRIPTION:
XS GIS Cut Line= 3
      1629605.03      6906438.02      1631205.00      6907288.00
      1631554.96      6907487.98
#Sta/Elev= 30
  3195.6 1700.11  3467.5 1693.00  3934.1 1684.94  4112.8 1677.00  4186.5 1676.17
  4192.2 1674.81  4290.8 1671.03  4475.1 1669.65  4724.7 1670.22  4769.5 1668.18
  4829.0 1669.79  4860.1 1667.62  4927.6 1666.58  4933.2 1664.14  4953.6 1662.02
  4954.6 1661.52  5000.8 1662.02  5004.5 1665.74  5042.6 1668.64  5101.6 1668.90
  5145.5 1666.81  5160.7 1667.81  5182.3 1676.38  5198.1 1678.32  5219.7 1684.83
  5249.2 1703.02  5257.1 1705.74  5272.2 1700.21  5278.7 1699.61  5410.4 1698.25
#Mann=3,-1,0
  3195.6    0.05       0  4953.6    0.05       0  5000.8    0.05       0
Bank Sta=4953.6,5000.8
Exp/Cntr=0.3,0.1

Type RM Length L Ch R = 1,20823,571,571,571
BEGIN DESCRIPTION:
Spring Creek 31.0
END DESCRIPTION:
XS GIS Cut Line= 3
      1630254.97      6907087.98      1631005.00      6907688.00
      1631204.99      6908037.99
#Sta/Elev= 30
  4043.4 1684.57  4114.7 1681.33  4185.1 1670.16  4213.9 1668.84  4449.2 1669.00
  4542.1 1665.32  4641.3 1669.68  4825.4 1669.92  4883.0 1669.10  4961.5 1664.40
  4988.2 1658.59  4989.2 1658.09  5035.5 1658.59  5039.2 1666.13  5070.8 1664.93
  5092.4 1667.99  5098.2 1670.53  5114.0 1671.86  5129.9 1678.12  5142.1 1685.06
  5188.2 1685.19  5216.3 1690.39  5318.5 1691.74  5326.4 1692.77  5334.3 1696.97
  5340.1 1701.94  5349.4 1704.54  5393.3 1708.20  5404.1 1713.65  5407.0 1713.65
#Mann=3,-1,0
  4043.4    0.05       0  4988.2    0.05       0  5035.5    0.05       0
Bank Sta=4988.2,5035.5
Exp/Cntr=0.3,0.1

Type RM Length L Ch R = 1,20252,437,437,437
BEGIN DESCRIPTION:
Spring Creek 30.0
END DESCRIPTION:
XS GIS Cut Line= 3
      1630155.01      6907138.03      1630505.00      6907888.00
      1631004.99      6908187.99
#Sta/Elev= 30
  4176.6 1685.71  4305.1 1679.62  4430.4 1664.77  4476.1 1667.33  4584.9 1668.38
  4865.8 1666.79  4907.7 1667.16  4949.8 1665.99  4958.5 1656.85  4959.5 1656.35
  5005.8 1656.85  5007.1 1658.62  5027.5 1660.10  5039.2 1665.15  5054.8 1667.25
  5096.9 1667.82  5179.1 1669.43  5202.5 1672.22  5223.8 1670.80  5251.1 1675.71
  5319.1 1676.47  5367.7 1685.03  5404.6 1688.94  5420.2 1688.13  5426.0 1691.14
  5457.1 1684.82  5505.7 1685.45  5542.6 1689.26  5573.7 1705.55  5587.3 1709.51
#Mann=6,-1,0
  4176.6    0.05       0  4865.8    0.12       0  4907.7    0.05       0
  4958.5    0.07       0  5005.8    0.05       0  5096.9    0.05       0
Bank Sta=4958.5,5005.8
Exp/Cntr=0.3,0.1

Type RM Length L Ch R = 1,19815,637,637,637
BEGIN DESCRIPTION:
Spring Creek 29.0
END DESCRIPTION:
XS GIS Cut Line= 3
      1629954.99      6907237.96      1630081.13      6907936.26
      1630404.97      6908387.96
#Sta/Elev= 30
  4288.9 1683.81  4390.6 1680.24  4486.5 1674.43  4553.1 1668.41  4563.3 1665.30
  4593.5 1663.36  4624.3 1663.92  4664.9 1667.05  4868.2 1664.70  4898.7 1665.43
  4919.0 1663.84  4940.1 1665.10  4946.1 1657.32  4947.1 1656.82  4993.4 1657.32
  4993.7 1659.77  4996.8 1658.58  5010.3 1659.60  5016.4 1658.43  5045.9 1662.74
  5160.6 1665.87  5375.0 1666.79  5461.0 1669.64  5490.5 1673.79  5505.1 1671.41
  5517.5 1675.64  5532.2 1678.10  5547.0 1685.99  5551.3 1691.64  5554.3 1691.64
#Mann=3,-1,0
  4288.9    0.05       0  4946.1    0.05       0  4993.4    0.05       0
Bank Sta=4946.1,4993.4
Exp/Cntr=0.3,0.1

Type RM Length L Ch R = 1,19178,783,783,783
BEGIN DESCRIPTION:
Spring Creek 28.0
END DESCRIPTION:
XS GIS Cut Line= 3
      1628805.04      6907588.02      1629505.00      6907888.00
      1630305.00      6908688.00
#Sta/Elev= 30
  4233.9 1690.90  4300.9 1687.90  4331.8 1685.35  4524.0 1679.22  4658.2 1670.03
  4705.3 1668.56  4857.6 1667.08  4904.8 1660.07  4910.2 1661.60  4928.3 1659.51
  4933.8 1661.61  4951.9 1658.64  4999.0 1659.22  5014.2 1657.25  5015.2 1656.75
  5061.6 1657.25  5066.1 1660.52  5136.9 1662.49  5193.4 1662.25  5235.8 1659.90
  5278.3 1662.32  5377.3 1663.83  5858.1 1665.09  5886.4 1666.79  5900.5 1669.07
  5928.8 1675.72  5985.4 1685.58  5999.5 1689.25  6070.2 1694.01  6126.8 1696.66
#Mann=3,-1,0
  4233.9    0.05       0  5014.2    0.05       0  5061.6    0.05       0
Bank Sta=5014.2,5061.6
Exp/Cntr=0.3,0.1

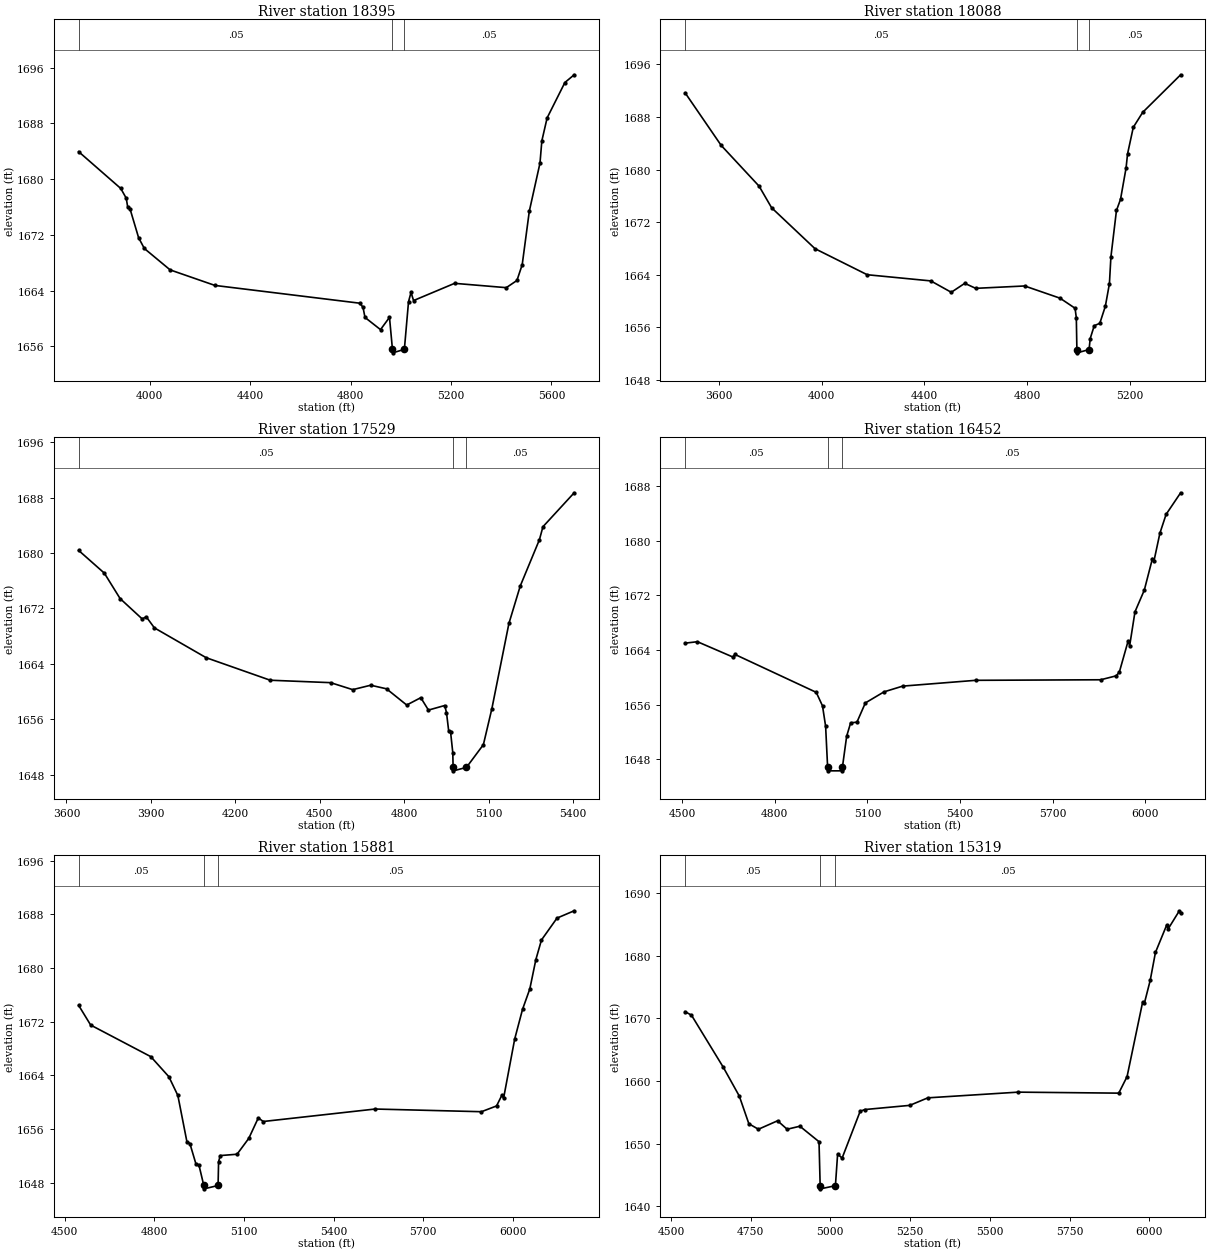
Type RM Length L Ch R = 1,18395,307,307,307
BEGIN DESCRIPTION:
Mapping XS 410c60be
END DESCRIPTION:
XS GIS Cut Line= 6
      1628555.53      6907920.64      1629465.24      6908420.64
      1629659.69      6908469.25      1629831.56      6908450.15
      1629996.49      6908405.01      1630263.88      6908691.50
#Sta/Elev= 30
  3716.3 1683.94  3884.2 1678.66  3906.0 1677.26  3911.7 1676.01  3921.1 1675.73
  3955.3 1671.59  3978.1 1670.05  4080.8 1666.98  4259.4 1664.75  4836.6 1662.20
  4849.3 1661.61  4857.2 1660.16  4919.0 1658.41  4954.8 1660.17  4966.6 1655.58
  4967.6 1655.08  5014.1 1655.58  5030.6 1662.41  5040.6 1663.75  5050.7 1662.58
  5214.2 1665.05  5420.1 1664.43  5462.6 1665.46  5483.6 1667.73  5511.9 1675.41
  5554.4 1682.30  5561.8 1685.49  5582.8 1688.78  5653.6 1693.86  5690.6 1694.97
#Mann=3,-1,0
  3716.3    0.05       0  4966.6    0.05       0  5014.1    0.05       0
Bank Sta=4966.6,5014.1
Exp/Cntr=0.3,0.1

Type RM Length L Ch R = 1,18088,559,559,559
BEGIN DESCRIPTION:
Spring Creek 27.0
END DESCRIPTION:
XS GIS Cut Line= 3
      1628297.69      6907951.88      1629605.00      6908738.00
      1629955.01      6908938.01
#Sta/Elev= 30
  3468.6 1691.67  3609.0 1683.67  3756.6 1677.47  3805.2 1674.19  3974.2 1667.96
  4177.3 1664.00  4424.9 1663.06  4504.5 1661.33  4557.0 1662.69  4599.7 1661.93
  4790.1 1662.29  4928.0 1660.43  4986.3 1658.90  4991.2 1657.46  4993.4 1652.62
  4994.4 1652.12  5040.9 1652.62  5045.2 1654.29  5061.0 1656.25  5082.6 1656.61
  5104.2 1659.21  5120.0 1662.63  5125.8 1666.70  5147.4 1673.77  5163.2 1675.46
  5184.8 1680.23  5190.6 1682.38  5212.9 1686.42  5249.6 1688.70  5397.2 1694.41
#Mann=3,-1,0
  3468.6    0.05       0  4993.4    0.05       0  5040.9    0.05       0
Bank Sta=4993.4,5040.9
Exp/Cntr=0.3,0.1

Type RM Length L Ch R = 1,17529,1077,1077,1077
BEGIN DESCRIPTION:
Spring Creek 26.0
END DESCRIPTION:
XS GIS Cut Line= 3
      1628193.54      6908292.16      1629255.00      6909138.00
      1629655.03      6909188.00
#Sta/Elev= 30
  3643.5 1680.37  3734.8 1677.09  3790.8 1673.42  3869.3 1670.48  3883.7 1670.79
  3912.6 1669.19  4096.7 1664.88  4324.1 1661.63  4538.7 1661.28  4617.2 1660.27
  4681.1 1660.91  4737.3 1660.39  4809.0 1658.05  4859.0 1659.11  4886.2 1657.32
  4943.9 1657.98  4950.3 1656.97  4958.3 1654.24  4964.7 1654.20  4972.7 1651.17
  4973.8 1649.05  4974.8 1648.55  5021.3 1649.05  5081.4 1652.33  5111.6 1657.54
  5172.1 1669.83  5212.4 1675.24  5280.4 1681.91  5293.0 1683.79  5403.9 1688.69
#Mann=3,-1,0
  3643.5    0.05       0  4973.8    0.05       0  5021.3    0.05       0
Bank Sta=4973.8,5021.3
Exp/Cntr=0.3,0.1

Type RM Length L Ch R = 1,16452,571,571,571
BEGIN DESCRIPTION:
Spring Creek 25.0
END DESCRIPTION:
XS GIS Cut Line= 4
      1627965.65      6909508.69      1628455.00      6909588.00
      1629063.98      6909690.85      1629551.68      6909754.71
#Sta/Elev= 30
  4509.5 1665.01  4549.4 1665.22  4663.7 1662.99  4670.9 1663.36  4934.3 1657.81
  4954.6 1655.83  4964.7 1652.84  4971.2 1646.82  4972.2 1646.32  5018.0 1646.32
  5019.0 1646.82  5032.9 1651.40  5045.8 1653.35  5066.1 1653.44  5093.4 1656.26
  5153.8 1657.88  5214.3 1658.72  5451.0 1659.57  5855.8 1659.65  5906.3 1660.23
  5916.3 1660.80  5944.5 1665.31  5949.6 1664.64  5966.8 1669.60  5997.0 1672.77
  6023.4 1677.40  6028.4 1677.06  6047.5 1681.10  6067.6 1683.86  6114.7 1687.02
#Mann=3,-1,0
  4509.5    0.05       0  4971.2    0.05       0  5019.0    0.05       0
Bank Sta=4971.2,5019
Exp/Cntr=0.3,0.1

Type RM Length L Ch R = 1,15881,562,562,562
BEGIN DESCRIPTION:
Spring Creek 24.0
END DESCRIPTION:
XS GIS Cut Line= 4
      1628004.98      6910138.00      1628455.00      6910088.00
      1628967.19      6909907.31      1629621.73      6909806.94
#Sta/Elev= 30
  4546.5 1674.45  4586.8 1671.51  4788.0 1666.80  4848.4 1663.81  4878.5 1661.01
  4908.7 1654.14  4918.8 1653.84  4938.9 1650.82  4949.0 1650.65  4965.3 1647.59
  4966.3 1647.09  5013.1 1647.59  5014.8 1651.15  5020.5 1652.05  5076.6 1652.25
  5115.9 1654.62  5147.7 1657.67  5164.1 1657.13  5538.6 1658.99  5894.3 1658.59
  5944.9 1659.45  5963.4 1661.11  5968.4 1660.60  6005.6 1669.43  6031.8 1673.85
  6056.2 1676.90  6076.4 1681.27  6095.1 1684.19  6147.2 1687.46  6204.6 1688.55
#Mann=3,-1,0
  4546.5    0.05       0  4965.3    0.03       0  5013.1    0.05       0
Bank Sta=4965.3,5013.1
Exp/Cntr=0.3,0.1

Type RM Length L Ch R = 1,15319,537,537,537
BEGIN DESCRIPTION:
Spring Creek 23.0
END DESCRIPTION:
XS GIS Cut Line= 4
      1628204.98      6910488.00      1628655.00      6910488.00
      1629049.23      6910093.77      1629577.31      6909952.89
#Sta/Elev= 30
  4544.4 1671.08  4564.4 1670.52  4664.4 1662.19  4714.4 1657.61  4744.4 1653.19
  4774.4 1652.32  4834.4 1653.67  4864.4 1652.32  4904.4 1652.80  4964.4 1650.33
  4968.0 1643.31  4969.0 1642.81  5015.8 1643.31  5022.7 1648.34  5036.9 1647.73
  5093.4 1655.18  5107.6 1655.46  5249.0 1656.13  5305.6 1657.33  5588.8 1658.24
  5904.4 1658.08  5930.5 1660.72  5979.4 1672.63  5984.6 1672.39  6003.0 1676.06
  6019.5 1680.53  6054.4 1684.86  6059.6 1684.31  6094.5 1687.18  6098.5 1686.85
#Mann=3,-1,0
  4544.4    0.05       0  4968.0    0.03       0  5015.8    0.05       0
Bank Sta=4968,5015.8
Exp/Cntr=0.3,0.1

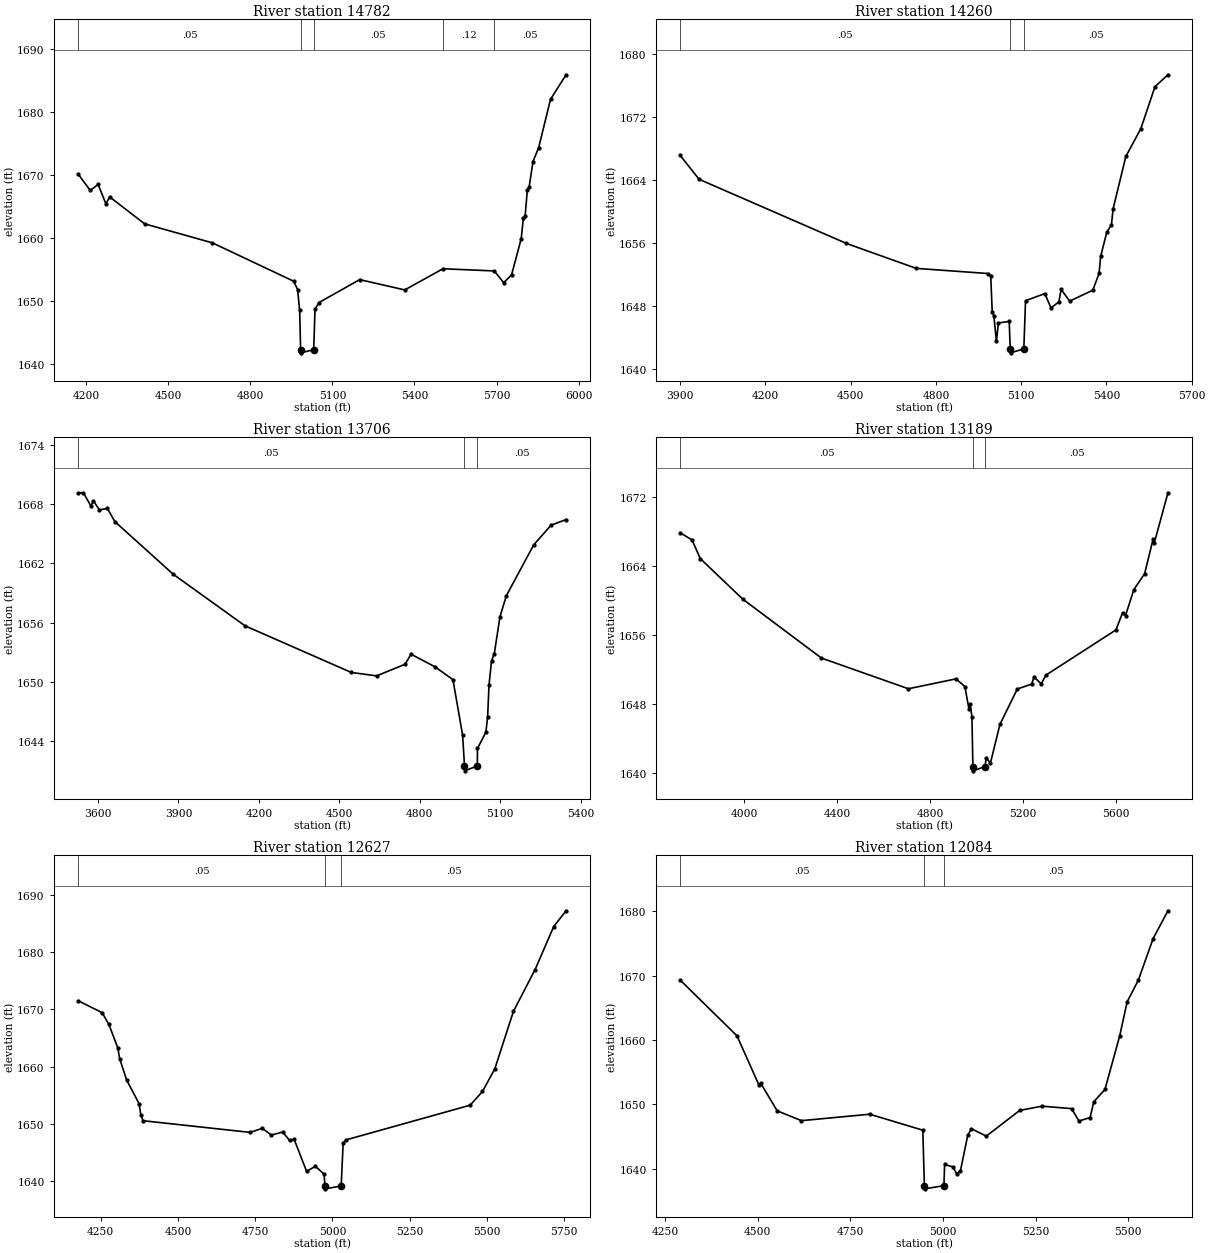
Type RM Length L Ch R = 1,14782,522,522,522
BEGIN DESCRIPTION:
Spring Creek 22.0
END DESCRIPTION:
XS GIS Cut Line= 3
      1628242.12      6911438.03      1628855.00      6910888.00
      1629605.03      6910287.98
#Sta/Elev= 30
  4170.4 1670.11  4214.6 1667.53  4243.0 1668.50  4271.4 1665.42  4285.6 1666.50
  4413.4 1662.22  4660.9 1659.20  4958.4 1653.09  4972.6 1651.77  4980.1 1648.44
  4983.6 1642.20  4984.6 1641.70  5031.5 1642.20  5036.3 1648.62  5050.7 1649.70
  5199.6 1653.35  5364.5 1651.71  5504.3 1655.08  5692.1 1654.73  5726.3 1652.86
  5755.1 1654.11  5790.3 1659.84  5798.3 1663.14  5804.7 1663.42  5812.7 1667.58
  5819.1 1668.01  5833.5 1672.14  5854.3 1674.36  5897.5 1682.03  5954.4 1685.94
#Mann=5,-1,0
  4170.4    0.05       0  4983.6    0.03       0  5031.5    0.05       0
  5504.3    0.12       0  5692.1    0.05       0
Bank Sta=4983.6,5031.5
Exp/Cntr=0.3,0.1

Type RM Length L Ch R = 1,14260,554,554,554
BEGIN DESCRIPTION:
Spring Creek 21.0
END DESCRIPTION:
XS GIS Cut Line= 3
      1628401.86      6911698.43      1629305.00      6911088.00
      1629605.01      6910537.99
#Sta/Elev= 30
  3900.0 1667.18  3966.7 1664.14  4485.2 1655.99  4730.9 1652.82  4982.6 1652.17
  4992.9 1651.91  4998.2 1647.27  5003.9 1646.80  5012.9 1643.56  5020.0 1645.89
  5058.0 1646.08  5061.5 1642.59  5062.5 1642.09  5109.4 1642.59  5115.4 1648.71
  5183.3 1649.62  5205.1 1647.79  5232.6 1648.57  5240.7 1650.15  5270.6 1648.66
  5352.2 1650.05  5374.1 1652.18  5379.8 1654.35  5401.6 1657.46  5417.7 1658.33
  5423.4 1660.37  5468.5 1667.05  5521.2 1670.58  5571.0 1675.92  5616.6 1677.42
#Mann=3,-1,0
  3900.0    0.05       0  5061.5    0.03       0  5109.4    0.05       0
Bank Sta=5061.5,5109.4
Exp/Cntr=0.3,0.1

Type RM Length L Ch R = 1,13706,517,517,517
BEGIN DESCRIPTION:
Spring Creek 20.0
END DESCRIPTION:
XS GIS Cut Line= 3
      1628384.53      6911802.58      1629705.00      6911138.00
      1629808.11      6910813.04
#Sta/Elev= 30
  3526.3 1669.14  3545.6 1669.17  3573.5 1667.83  3582.8 1668.35  3605.2 1667.44
  3634.9 1667.58  3662.8 1666.25  3880.4 1660.91  4148.2 1655.68  4544.3 1650.95
  4639.1 1650.60  4745.1 1651.78  4767.4 1652.80  4856.7 1651.52  4923.7 1650.22
  4959.8 1644.57  4966.7 1641.47  4967.7 1640.97  5014.6 1641.47  5015.1 1643.24
  5046.5 1644.89  5053.0 1646.45  5058.2 1649.69  5067.5 1652.11  5078.0 1652.87
  5099.0 1656.60  5122.8 1658.73  5224.9 1663.89  5289.4 1665.88  5345.5 1666.45
#Mann=3,-1,0
  3526.3    0.05       0  4966.7    0.05       0  5014.6    0.05       0
Bank Sta=4966.7,5014.6
Exp/Cntr=0.3,0.1

Type RM Length L Ch R = 1,13189,562,562,562
BEGIN DESCRIPTION:
Spring Creek 19.0
END DESCRIPTION:
XS GIS Cut Line= 3
      1628494.48      6911797.24      1629755.00      6911588.00
      1630555.01      6911788.00
#Sta/Elev= 30
  3722.9 1667.89  3774.1 1667.06  3809.7 1664.89  3992.6 1660.18  4331.6 1653.33
  4706.7 1649.76  4911.8 1650.91  4950.0 1650.02  4967.7 1647.41  4972.7 1647.98
  4980.4 1646.51  4984.6 1640.72  4985.7 1640.22  5037.3 1640.72  5041.9 1641.76
  5059.9 1641.10  5101.2 1645.62  5175.9 1649.73  5237.7 1650.30  5248.1 1651.13
  5279.0 1650.33  5299.6 1651.35  5601.1 1656.60  5629.4 1658.58  5642.3 1658.27
  5678.4 1661.29  5724.8 1663.14  5760.9 1667.12  5766.0 1666.68  5825.3 1672.54
#Mann=3,-1,0
  3722.9    0.05       0  4984.6    0.03       0  5037.3    0.05       0
Bank Sta=4984.6,5037.3
Exp/Cntr=0.3,0.1

Type RM Length L Ch R = 1,12627,543,543,543
BEGIN DESCRIPTION:
Spring Creek 18.0
END DESCRIPTION:
XS GIS Cut Line= 3
      1629205.02      6912387.99      1629955.00      6912038.00
      1630705.01      6911988.00
#Sta/Elev= 30
  4177.2 1671.50  4254.4 1669.42  4276.5 1667.36  4305.7 1663.18  4311.2 1661.40
  4334.0 1657.63  4374.2 1653.50  4379.8 1651.53  4386.8 1650.53  4733.7 1648.49
  4773.1 1649.20  4802.2 1648.02  4839.3 1648.55  4861.4 1647.08  4876.3 1647.27
  4916.5 1641.67  4944.9 1642.57  4973.3 1641.18  4975.7 1639.12  4976.8 1638.62
  5028.4 1639.12  5034.9 1646.67  5044.9 1647.19  5445.8 1653.24  5485.9 1655.64
  5526.0 1659.62  5586.1 1669.65  5656.3 1676.96  5716.4 1684.46  5756.5 1687.23
#Mann=3,-1,0
  4177.2    0.05       0  4975.7    0.03       0  5028.4    0.05       0
Bank Sta=4975.7,5028.4
Exp/Cntr=0.3,0.1

Type RM Length L Ch R = 1,12084,559,559,559
BEGIN DESCRIPTION:
Spring Creek 17.0
END DESCRIPTION:
XS GIS Cut Line= 3
      1629304.96      6912387.99      1630005.00      6912538.00
      1630604.97      6912538.00
#Sta/Elev= 30
  4291.1 1669.30  4444.5 1660.63  4503.3 1653.03  4508.5 1653.27  4552.8 1648.99
  4618.4 1647.46  4802.5 1648.46  4945.7 1645.98  4949.9 1637.37  4951.0 1636.87
  5002.7 1637.37  5004.5 1640.66  5027.0 1640.27  5037.0 1639.22  5047.0 1639.63
  5067.0 1645.22  5077.0 1646.20  5117.0 1645.06  5207.0 1649.05  5267.0 1649.71
  5347.0 1649.33  5367.0 1647.40  5397.0 1647.95  5407.0 1650.41  5437.0 1652.30
  5477.0 1660.68  5497.0 1665.94  5527.0 1669.27  5567.0 1675.75  5607.0 1680.06
#Mann=3,-1,0
  4291.1    0.05       0  4949.9    0.03       0  5002.7    0.05       0
Bank Sta=4949.9,5002.7
Exp/Cntr=0.3,0.1