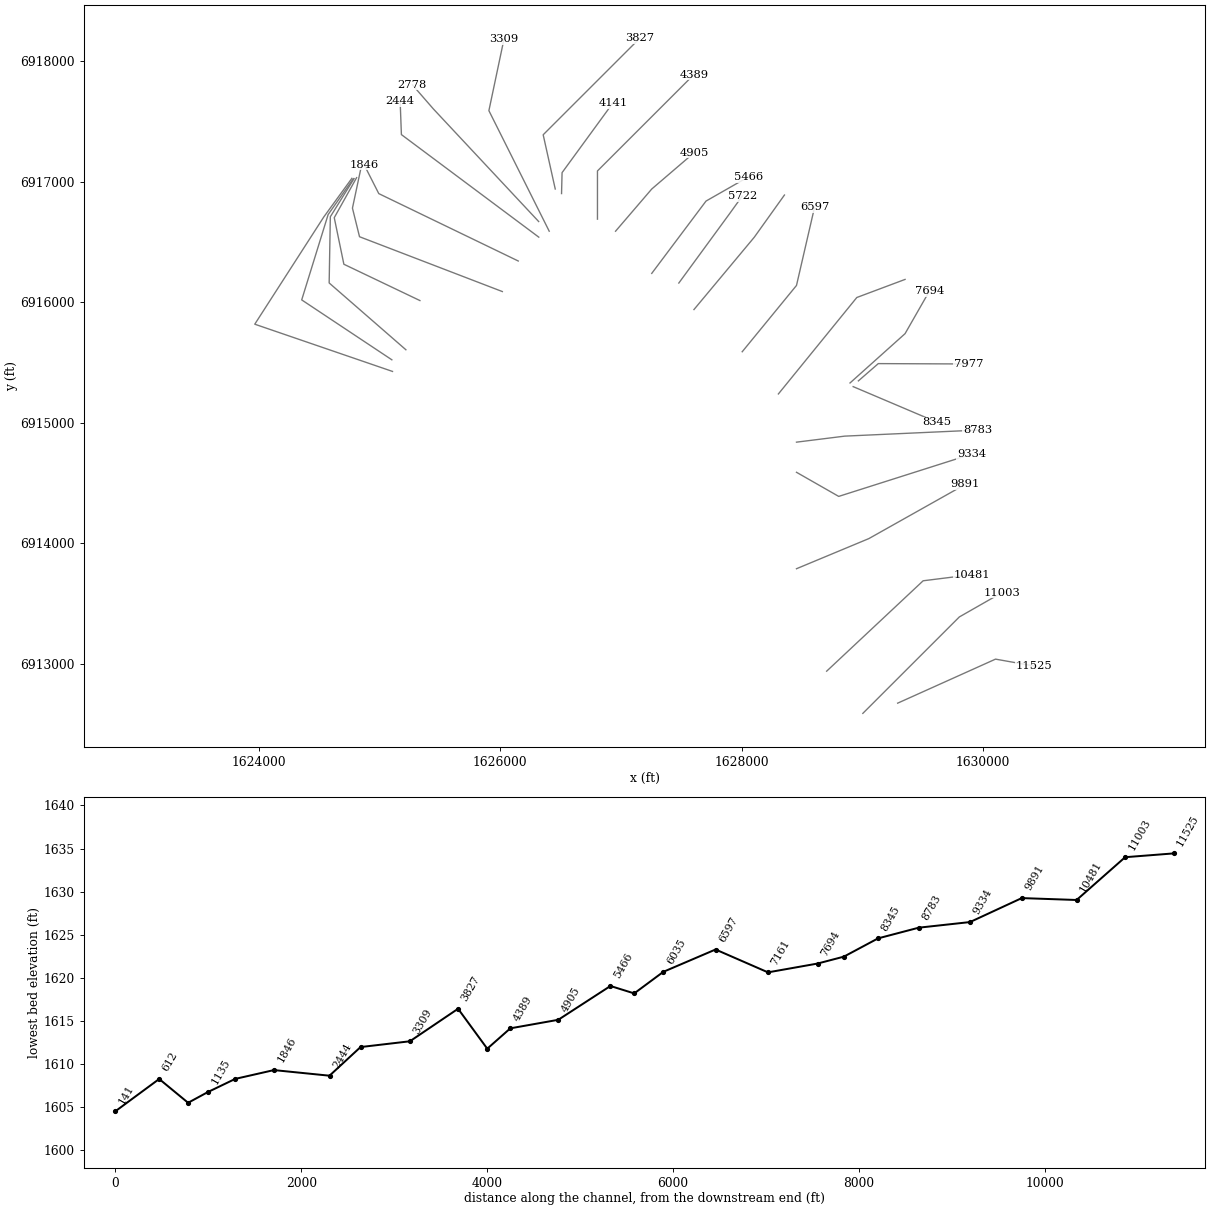
HEC-RAS study Spring Creek.prj: Spring Creek Base Level Engineering

--- Spring Creek.g01 (geometry) --- (continued)

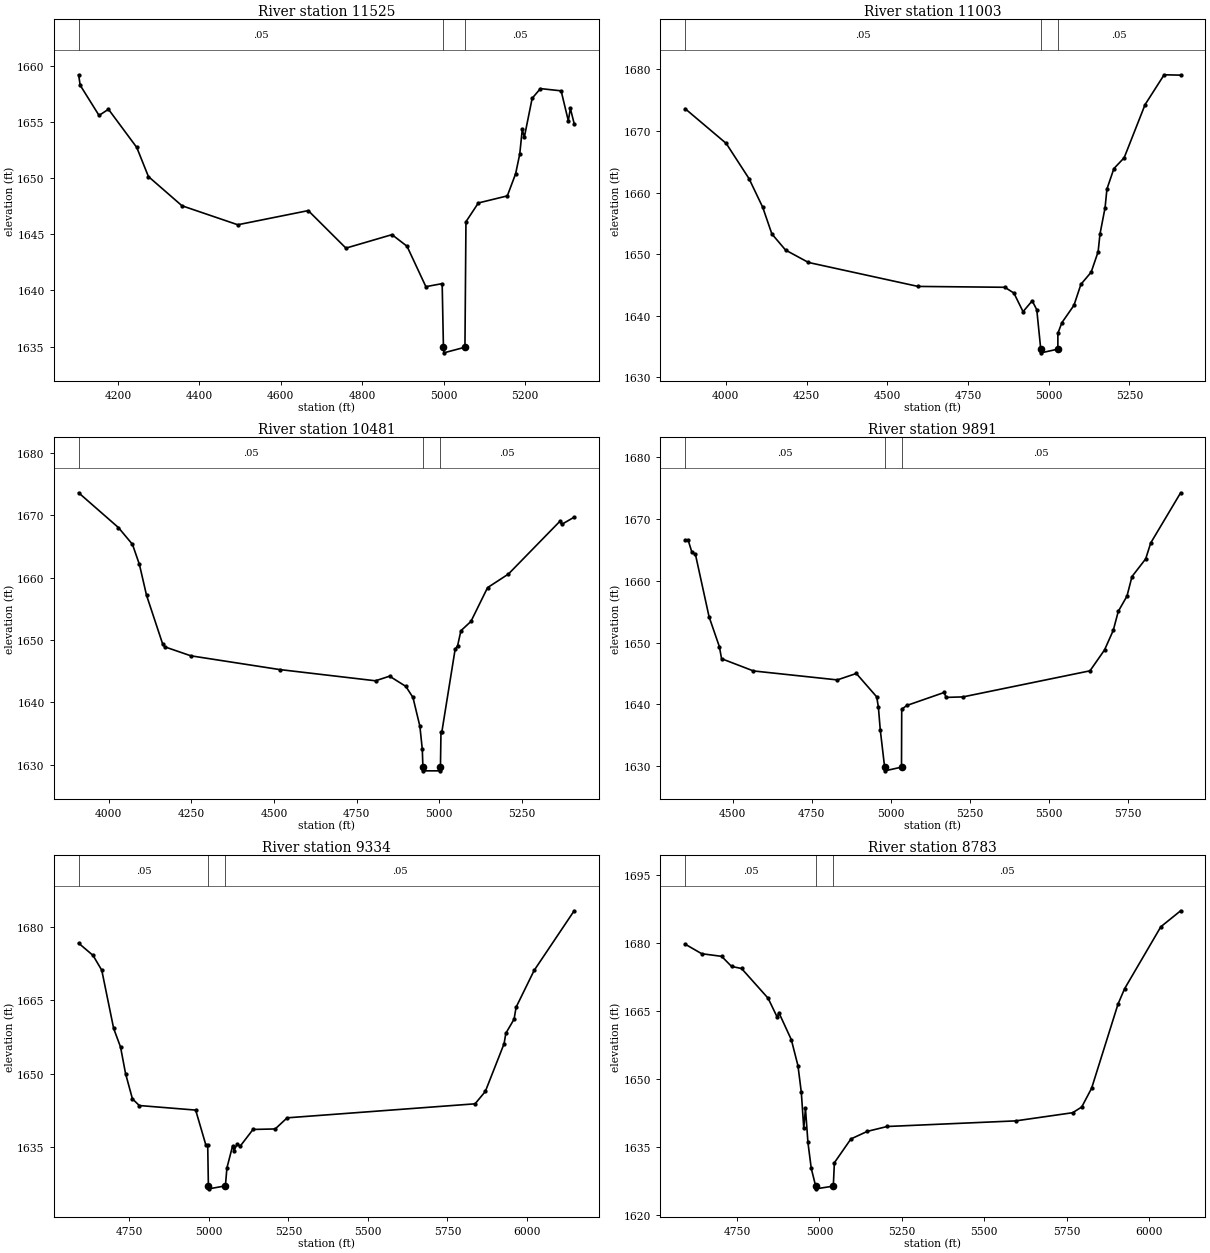
Type RM Length L Ch R = 1,11525,522,522,522
BEGIN DESCRIPTION:
Spring Creek 16.0
END DESCRIPTION:
XS GIS Cut Line= 3
      1629293.70      6912672.73      1630105.00      6913038.00
      1630426.53      6912980.91
#Sta/Elev= 30
  4103.7 1659.19  4107.5 1658.26  4153.8 1655.57  4176.9 1656.12  4246.4 1652.72
  4275.0 1650.13  4357.4 1647.53  4494.3 1645.84  4667.3 1647.10  4759.8 1643.76
  4872.8 1644.96  4909.7 1643.93  4956.0 1640.33  4996.0 1640.60  4999.1 1634.94
  5000.2 1634.44  5051.9 1634.94  5054.4 1646.11  5084.8 1647.78  5155.9 1648.41
  5176.3 1650.38  5186.4 1652.13  5192.6 1654.32  5197.6 1653.63  5216.9 1657.10
  5237.2 1657.96  5288.0 1657.76  5305.6 1655.10  5310.7 1656.19  5320.0 1654.84
#Mann=3,-1,0
  4103.7    0.05       0  4999.1    0.03       0  5051.9    0.05       0
Bank Sta=4999.1,5051.9
Exp/Cntr=0.3,0.1

Type RM Length L Ch R = 1,11003,522,522,522
BEGIN DESCRIPTION:
Spring Creek 15.0
END DESCRIPTION:
XS GIS Cut Line= 3
      1629004.99      6912587.99      1629805.00      6913388.00
      1630155.00      6913588.00
#Sta/Elev= 30
  3874.0 1673.63  4001.3 1667.99  4072.0 1662.27  4114.4 1657.62  4142.7 1653.30
  4185.1 1650.68  4255.9 1648.67  4595.3 1644.78  4864.0 1644.64  4892.2 1643.70
  4920.5 1640.68  4948.8 1642.44  4963.0 1641.00  4975.3 1634.60  4976.4 1634.00
  5028.3 1634.60  5028.4 1637.18  5040.7 1638.89  5078.1 1641.71  5099.7 1645.12
  5131.4 1647.09  5153.0 1650.41  5158.7 1653.27  5174.5 1657.56  5180.3 1660.60
  5201.9 1663.91  5233.6 1665.66  5298.4 1674.29  5357.4 1679.13  5408.5 1679.07
#Mann=3,-1,0
  3874.0    0.05       0  4975.3    0.05       0  5028.3    0.05       0
Bank Sta=4975.3,5028.3
Exp/Cntr=0.3,0.1

Type RM Length L Ch R = 1,10481,590,590,590
BEGIN DESCRIPTION:
Spring Creek 14.0
END DESCRIPTION:
XS GIS Cut Line= 3
      1628705.02      6912938.02      1629505.00      6913688.00
      1629905.03      6913738.00
#Sta/Elev= 30
  3908.9 1673.57  4029.3 1668.00  4071.8 1665.31  4092.8 1662.10  4114.3 1657.17
  4163.6 1649.29  4170.5 1648.88  4248.6 1647.46  4517.2 1645.26  4807.4 1643.46
  4849.9 1644.20  4899.2 1642.56  4920.7 1640.79  4941.7 1636.17  4949.0 1632.46
  4950.8 1629.64  4951.9 1629.04  5002.8 1629.04  5003.9 1629.64  5005.5 1635.23
  5008.0 1635.23  5048.3 1648.49  5055.8 1649.08  5065.9 1651.48  5096.2 1652.97
  5146.5 1658.38  5209.5 1660.55  5365.7 1669.02  5370.8 1668.51  5408.6 1669.66
#Mann=3,-1,0
  3908.9    0.05       0  4950.8    0.05       0  5003.9    0.05       0
Bank Sta=4950.8,5003.9
Exp/Cntr=0.3,0.1

Type RM Length L Ch R = 1,9891,557,557,557
BEGIN DESCRIPTION:
Spring Creek 13.0
END DESCRIPTION:
XS GIS Cut Line= 3
      1628454.97      6913787.99      1629055.00      6914038.00
      1629854.99      6914488.00
#Sta/Elev= 30
  4349.4 1666.58  4358.6 1666.65  4371.1 1664.59  4381.9 1664.32  4425.3 1654.17
  4457.8 1649.35  4464.8 1647.40  4565.6 1645.42  4831.0 1643.97  4891.1 1645.01
  4955.6 1641.23  4961.0 1639.57  4966.9 1635.89  4980.7 1629.86  4981.7 1629.26
  5034.1 1629.86  5034.8 1639.22  5050.7 1639.83  5169.3 1641.94  5175.0 1641.14
  5228.6 1641.22  5630.5 1645.44  5676.4 1648.81  5704.1 1651.98  5720.0 1655.06
  5747.4 1657.51  5763.4 1660.69  5806.7 1663.55  5822.7 1666.13  5917.3 1674.24
#Mann=3,-1,0
  4349.4    0.05       0  4980.7    0.03       0  5034.1    0.05       0
Bank Sta=4980.7,5034.1
Exp/Cntr=0.3,0.1

Type RM Length L Ch R = 1,9334,551,551,551
BEGIN DESCRIPTION:
Spring Creek 12.0
END DESCRIPTION:
XS GIS Cut Line= 3
      1628455.04      6914587.98      1628805.00      6914388.00
      1629905.00      6914738.00
#Sta/Elev= 30
  4590.9 1676.61  4636.2 1674.11  4663.6 1671.09  4701.0 1659.20  4722.6 1655.42
  4738.4 1649.99  4760.0 1644.83  4781.6 1643.48  4958.7 1642.55  4991.1 1635.35
  4996.6 1635.35  4998.7 1627.08  4999.8 1626.48  5052.2 1627.08  5056.9 1630.74
  5074.5 1635.16  5079.8 1634.29  5088.4 1635.56  5098.9 1635.21  5139.0 1638.60
  5208.7 1638.70  5246.2 1640.97  5836.9 1643.83  5869.1 1646.36  5927.9 1656.07
  5933.6 1658.23  5959.4 1661.10  5965.8 1663.54  6022.4 1671.04  6148.3 1683.22
#Mann=3,-1,0
  4590.9    0.05       0  4998.7    0.05       0  5052.2    0.05       0
Bank Sta=4998.7,5052.2
Exp/Cntr=0.3,0.1

Type RM Length L Ch R = 1,8783,438,438,438
BEGIN DESCRIPTION:
Spring Creek 11.0
END DESCRIPTION:
XS GIS Cut Line= 3
      1628454.95      6914837.99      1628855.00      6914888.00
      1629955.00      6914938.00
#Sta/Elev= 30
  4592.0 1679.80  4642.4 1677.69  4702.9 1677.11  4733.1 1674.88  4763.4 1674.43
  4844.0 1667.87  4871.7 1663.68  4876.7 1664.69  4914.5 1658.72  4934.7 1652.96
  4944.8 1647.10  4952.3 1639.15  4957.4 1643.57  4964.9 1636.06  4975.0 1630.33
  4988.4 1626.43  4989.5 1625.83  5041.9 1626.43  5045.2 1631.59  5095.3 1636.83
  5145.3 1638.51  5205.4 1639.58  5595.8 1640.82  5768.5 1642.62  5796.0 1643.88
  5826.0 1648.01  5906.1 1666.56  5926.1 1669.96  6036.2 1683.64  6096.3 1687.16
#Mann=3,-1,0
  4592.0    0.05       0  4988.4    0.05       0  5041.9    0.05       0
Bank Sta=4988.4,5041.9
Exp/Cntr=0.3,0.1

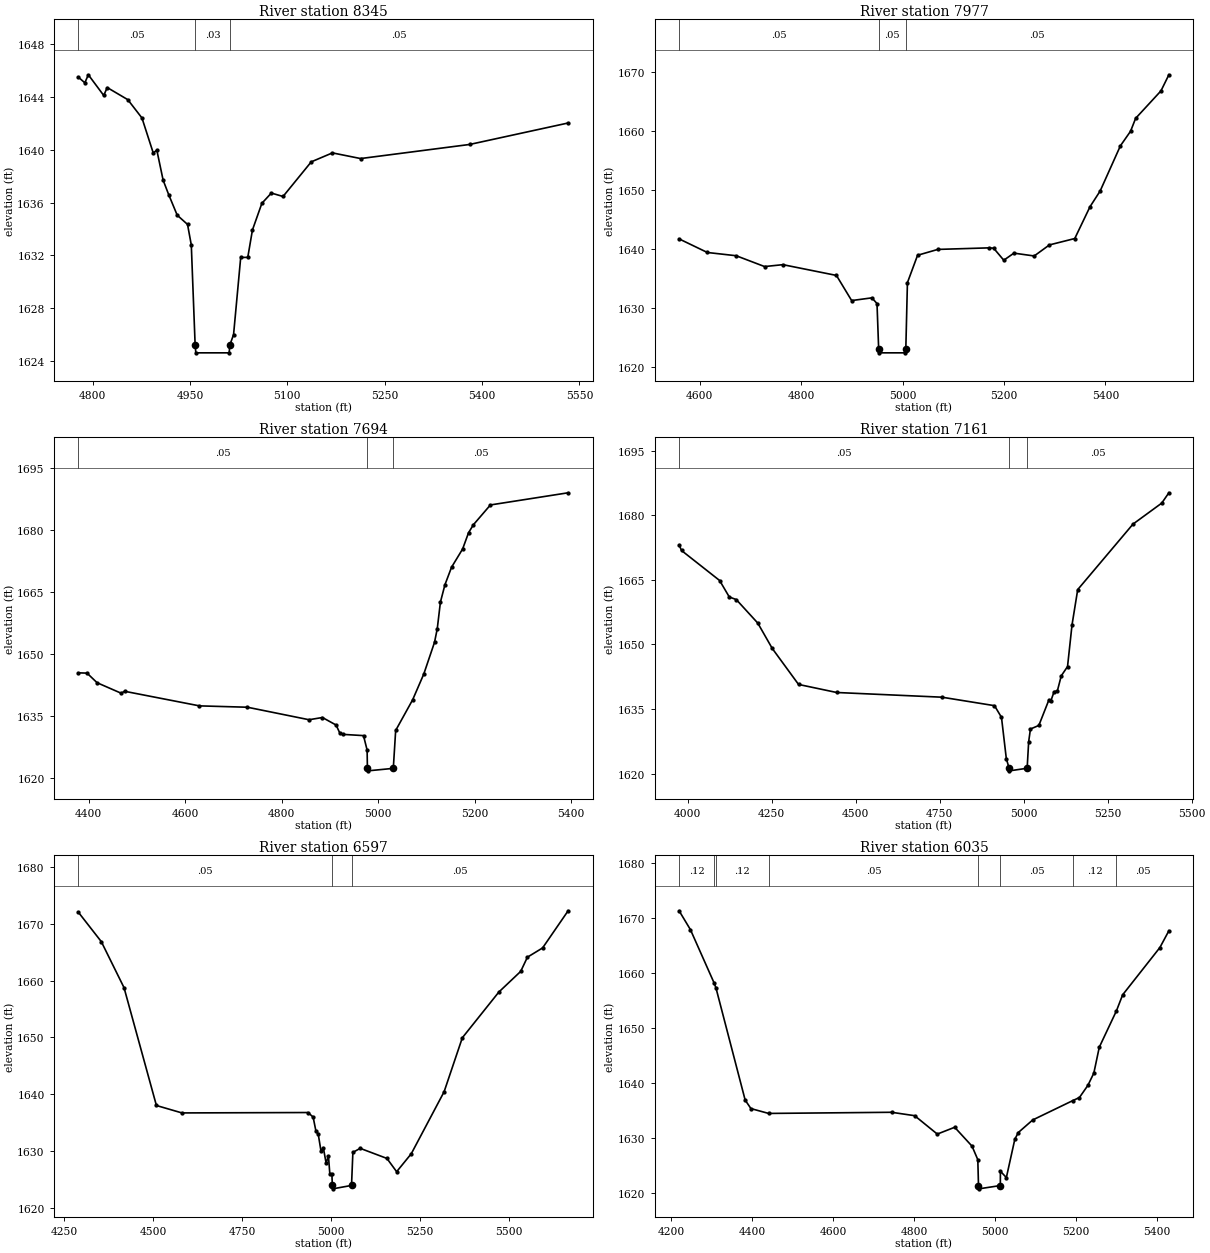
Type RM Length L Ch R = 1,8345,368,368,368
BEGIN DESCRIPTION:
Mapping XS 356e7ec0
END DESCRIPTION:
XS GIS Cut Line= 2
      1628924.83      6915298.61      1629619.22      6915003.49
#Sta/Elev= 30
  4778.1 1645.52  4788.1 1645.09  4793.5 1645.70  4817.2 1644.13  4822.6 1644.73
  4854.3 1643.81  4876.1 1642.42  4893.5 1639.76  4899.0 1639.98  4908.7 1637.70
  4917.2 1636.61  4930.4 1635.04  4946.3 1634.34  4952.1 1632.78  4958.0 1625.19
  4959.1 1624.59  5010.4 1624.59  5011.5 1625.19  5017.2 1625.97  5028.2 1631.83
  5039.1 1631.84  5046.3 1633.92  5060.8 1635.94  5075.4 1636.72  5093.4 1636.46
  5136.9 1639.09  5169.5 1639.77  5212.9 1639.34  5380.9 1640.41  5532.6 1642.04
#Mann=3,-1,0
  4778.1    0.05       0  4958.0    0.03       0  5011.5    0.05       0
Bank Sta=4958,5011.5
Exp/Cntr=0.3,0.1

Type RM Length L Ch R = 1,7977,283,283,283
BEGIN DESCRIPTION:
Mapping XS 8604558d
END DESCRIPTION:
XS GIS Cut Line= 3
      1628968.19      6915346.33      1629133.15      6915489.59
      1629880.56      6915486.61
#Sta/Elev= 30
  4559.2 1641.74  4614.9 1639.44  4671.8 1638.89  4727.8 1637.06  4764.0 1637.38
  4869.5 1635.56  4899.5 1631.31  4939.5 1631.77  4949.5 1630.80  4952.8 1623.07
  4953.9 1622.47  5005.2 1622.47  5006.3 1623.07  5009.5 1634.34  5029.5 1638.97
  5069.5 1639.96  5169.5 1640.22  5179.5 1640.17  5199.5 1638.13  5219.5 1639.33
  5259.5 1638.85  5289.5 1640.72  5339.5 1641.80  5369.5 1647.17  5389.5 1649.83
  5429.5 1657.48  5449.5 1659.94  5459.5 1662.12  5509.5 1666.77  5525.1 1669.49
#Mann=3,-1,0
  4559.2    0.05       0  4952.8    0.05       0  5006.3    0.05       0
Bank Sta=4952.8,5006.3
Exp/Cntr=0.3,0.1

Type RM Length L Ch R = 1,7694,533,533,533
BEGIN DESCRIPTION:
Spring Creek 10.0
END DESCRIPTION:
XS GIS Cut Line= 3
      1628898.78      6915329.00      1629355.00      6915738.00
      1629554.99      6916087.98
#Sta/Elev= 30
  4378.3 1645.43  4396.3 1645.36  4417.2 1643.03  4467.2 1640.48  4474.1 1640.96
  4629.5 1637.42  4729.0 1637.09  4856.7 1634.06  4884.5 1634.60  4912.9 1632.77
  4920.4 1630.87  4927.1 1630.51  4969.7 1630.21  4977.2 1626.70  4977.8 1622.27
  4978.9 1621.67  5031.5 1622.27  5036.4 1631.46  5071.6 1638.89  5094.7 1645.13
  5117.0 1652.84  5122.7 1656.15  5129.2 1662.57  5138.6 1666.79  5152.3 1671.03
  5175.3 1675.46  5187.5 1679.38  5197.6 1681.33  5232.9 1686.13  5394.1 1689.08
#Mann=3,-1,0
  4378.3    0.05       0  4977.8    0.05       0  5031.5    0.05       0
Bank Sta=4977.8,5031.5
Exp/Cntr=0.3,0.1

Type RM Length L Ch R = 1,7161,564,564,564
BEGIN DESCRIPTION:
Spring Creek 9.0
END DESCRIPTION:
XS GIS Cut Line= 3
      1628304.98      6915237.97      1628955.00      6916038.00
      1629354.99      6916188.00
#Sta/Elev= 30
  3974.2 1673.11  3981.4 1671.81  4094.9 1664.84  4123.6 1661.02  4144.5 1660.41
  4208.4 1654.96  4251.5 1649.07  4329.8 1640.71  4443.3 1638.84  4756.5 1637.75
  4913.1 1635.78  4933.9 1633.07  4948.3 1623.48  4956.6 1621.25  4957.7 1620.65
  5010.3 1621.25  5014.8 1627.41  5020.1 1630.36  5045.1 1631.19  5075.3 1637.17
  5080.7 1636.85  5090.5 1639.04  5100.2 1639.20  5111.8 1642.70  5130.5 1644.86
  5143.9 1654.55  5160.8 1662.73  5325.4 1677.94  5410.9 1682.81  5432.2 1685.21
#Mann=3,-1,0
  3974.2    0.05       0  4956.6    0.05       0  5010.3    0.05       0
Bank Sta=4956.6,5010.3
Exp/Cntr=0.3,0.1

Type RM Length L Ch R = 1,6597,562,562,562
BEGIN DESCRIPTION:
Spring Creek 8.0
END DESCRIPTION:
XS GIS Cut Line= 3
      1628005.02      6915588.02      1628455.00      6916138.00
      1628605.00      6916788.01
#Sta/Elev= 30
  4289.6 1672.06  4354.2 1666.87  4418.1 1658.76  4509.2 1637.99  4581.0 1636.68
  4935.6 1636.75  4950.0 1635.95  4957.9 1633.47  4964.3 1632.96  4972.2 1629.93
  4978.7 1630.56  4986.6 1627.80  4993.0 1629.14  4997.0 1625.92  5002.8 1625.92
  5004.0 1623.90  5005.1 1623.30  5058.0 1623.90  5061.8 1629.72  5082.3 1630.44
  5157.6 1628.66  5184.9 1626.32  5226.0 1629.48  5318.4 1640.41  5369.7 1649.93
  5472.3 1657.98  5533.9 1661.63  5552.7 1664.13  5595.4 1665.76  5667.3 1672.31
#Mann=3,-1,0
  4289.6    0.05       0  5004.0    0.05       0  5058.0    0.05       0
Bank Sta=5004,5058
Exp/Cntr=0.3,0.1

Type RM Length L Ch R = 1,6035,313,313,313
BEGIN DESCRIPTION:
Spring Creek 7.0
END DESCRIPTION:
XS GIS Cut Line= 3
      1627604.98      6915937.98      1628105.00      6916538.00
      1628355.02      6916888.03
#Sta/Elev= 30
  4218.8 1671.34  4246.8 1667.91  4304.9 1658.28  4309.9 1657.32  4382.2 1636.87
  4396.5 1635.32  4440.3 1634.44  4744.1 1634.65  4801.3 1634.03  4857.3 1630.68
  4900.3 1631.92  4943.2 1628.48  4957.5 1626.02  4959.2 1621.31  4960.3 1620.71
  5013.2 1621.31  5013.4 1623.92  5028.1 1622.76  5049.0 1629.73  5057.6 1630.96
  5093.2 1633.25  5191.9 1636.76  5208.8 1637.34  5229.7 1639.55  5244.4 1641.78
  5257.9 1646.50  5300.3 1653.12  5315.7 1656.04  5407.8 1664.65  5430.0 1667.70
#Mann=8,-1,0
  4218.8    0.12       0  4304.9    0.05       0  4309.9    0.12       0
  4440.3    0.05       0  4959.2    0.05       0  5013.2    0.05       0
  5191.9    0.12       0  5300.3    0.05       0
Bank Sta=4959.2,5013.2
Exp/Cntr=0.3,0.1

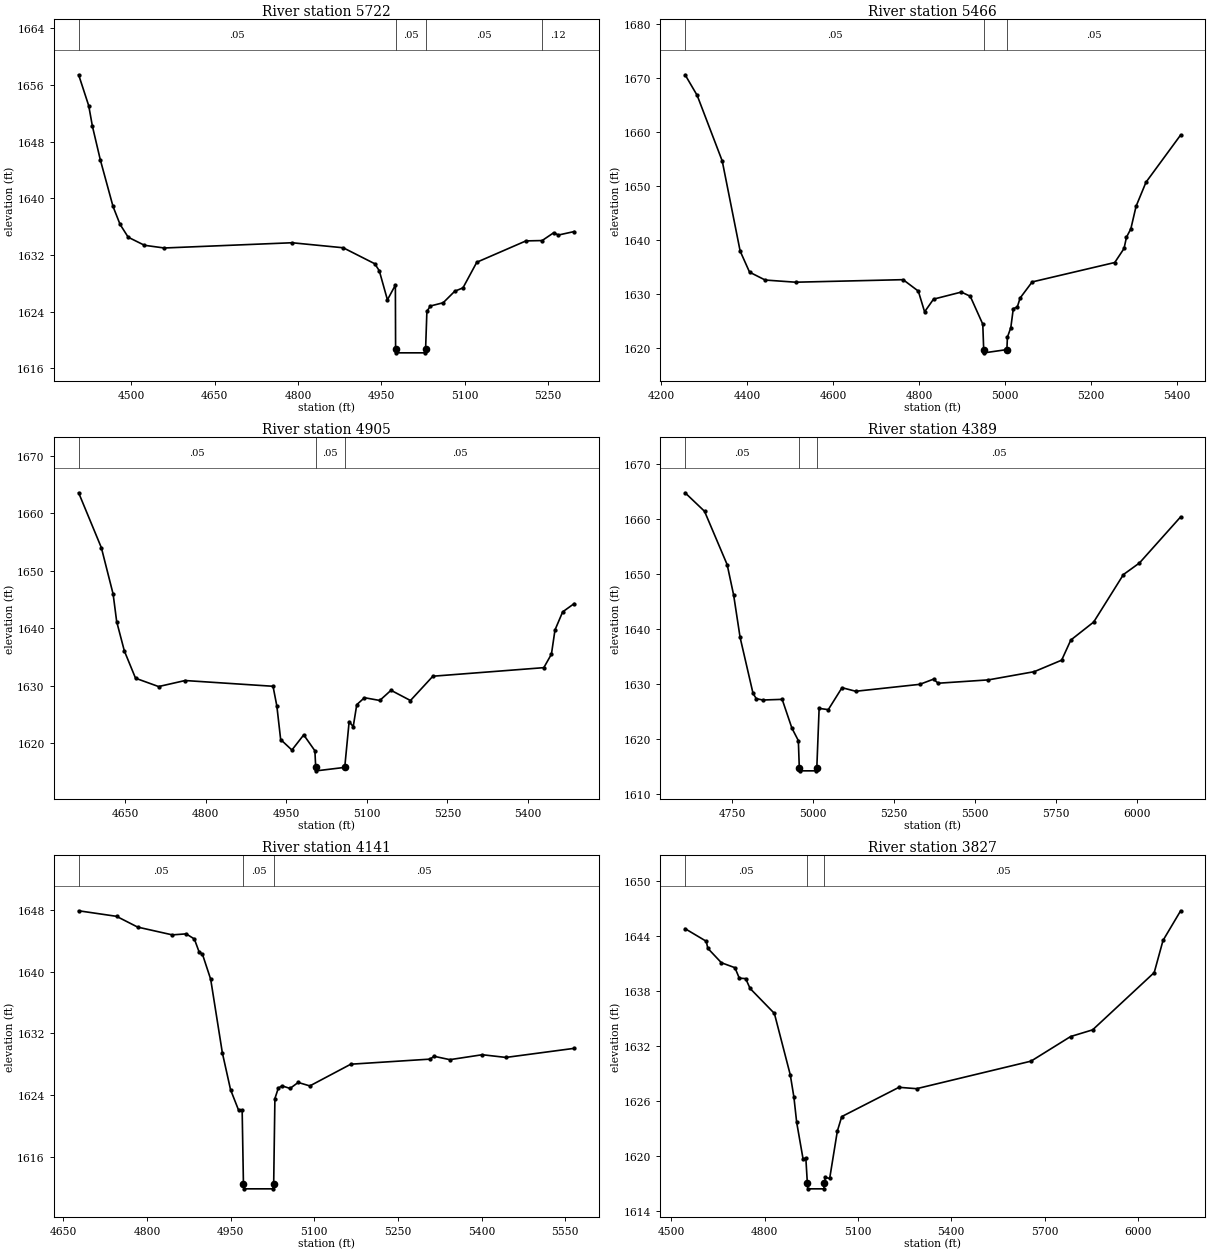
Type RM Length L Ch R = 1,5722,256,256,256
BEGIN DESCRIPTION:
Mapping XS 522a8a9f
END DESCRIPTION:
XS GIS Cut Line= 3
      1627479.52      6916158.01      1627904.85      6916739.59
      1628004.70      6916878.51
#Sta/Elev= 30
  4405.3 1657.46  4423.5 1653.08  4430.1 1650.19  4444.3 1645.46  4467.2 1638.87
  4479.8 1636.35  4494.5 1634.53  4523.8 1633.39  4559.4 1633.01  4789.3 1633.75
  4881.4 1633.04  4938.0 1630.79  4946.2 1629.81  4960.9 1625.69  4975.2 1627.77
  4975.6 1618.81  4976.7 1618.21  5028.5 1618.21  5029.6 1618.81  5031.9 1624.05
  5038.1 1624.82  5061.2 1625.28  5082.1 1626.91  5096.8 1627.38  5121.7 1631.00
  5210.1 1634.01  5239.3 1634.06  5260.0 1635.16  5268.6 1634.84  5296.9 1635.33
#Mann=4,-1,0
  4405.3    0.05       0  4975.6    0.05       0  5029.6    0.05       0
  5239.3    0.12       0
Bank Sta=4975.6,5029.6
Exp/Cntr=0.3,0.1

Type RM Length L Ch R = 1,5466,561,561,561
BEGIN DESCRIPTION:
Spring Creek 6.0
END DESCRIPTION:
XS GIS Cut Line= 3
      1627255.02      6916238.02      1627705.00      6916838.00
      1628055.01      6917038.01
#Sta/Elev= 30
  4255.0 1670.60  4283.1 1666.78  4341.4 1654.63  4383.1 1637.93  4405.0 1634.02
  4441.4 1632.56  4512.3 1632.16  4762.3 1632.63  4797.7 1630.51  4812.3 1626.67
  4833.1 1629.02  4897.7 1630.33  4918.5 1629.56  4947.7 1624.38  4949.8 1619.67
  4950.9 1619.07  5003.8 1619.67  5005.0 1621.97  5012.9 1623.73  5018.7 1627.26
  5028.0 1627.56  5034.5 1629.22  5062.6 1632.21  5254.8 1635.81  5276.4 1638.41
  5282.1 1640.51  5292.2 1642.04  5304.4 1646.23  5327.5 1650.69  5408.1 1659.44
#Mann=3,-1,0
  4255.0    0.05       0  4949.8    0.05       0  5003.8    0.05       0
Bank Sta=4949.8,5003.8
Exp/Cntr=0.3,0.1

Type RM Length L Ch R = 1,4905,516,516,516
BEGIN DESCRIPTION:
Spring Creek 5.0
END DESCRIPTION:
XS GIS Cut Line= 3
      1626954.98      6916587.98      1627255.00      6916938.00
      1627605.01      6917238.01
#Sta/Elev= 30
  4563.8 1663.55  4606.1 1653.99  4628.0 1645.91  4634.6 1641.12  4648.9 1636.01
  4669.7 1631.27  4712.6 1629.82  4761.9 1630.87  4925.5 1629.87  4932.6 1626.44
  4939.7 1620.60  4960.6 1618.77  4982.6 1621.41  5003.4 1618.64  5004.9 1615.75
  5006.0 1615.15  5058.9 1615.75  5067.1 1623.72  5074.7 1622.84  5081.3 1626.67
  5095.6 1627.88  5124.1 1627.40  5145.0 1629.17  5181.2 1627.39  5222.9 1631.62
  5429.3 1633.11  5443.5 1635.46  5450.1 1639.67  5464.4 1642.82  5485.8 1644.26
#Mann=3,-1,0
  4563.8    0.05       0  5004.9    0.05       0  5058.9    0.05       0
Bank Sta=5004.9,5058.9
Exp/Cntr=0.3,0.1

Type RM Length L Ch R = 1,4389,248,248,248
BEGIN DESCRIPTION:
Spring Creek 4.0
END DESCRIPTION:
XS GIS Cut Line= 3
      1626805.00      6916687.96      1626805.00      6917088.00
      1627604.99      6917887.99
#Sta/Elev= 30
  4604.9 1664.69  4664.9 1661.33  4734.9 1651.63  4754.9 1646.11  4774.9 1638.40
  4814.9 1628.22  4824.9 1627.28  4844.9 1627.03  4904.9 1627.15  4934.9 1621.93
  4954.9 1619.65  4957.8 1614.76  4959.0 1614.16  5010.9 1614.16  5012.0 1614.76
  5019.1 1625.51  5047.4 1625.28  5089.8 1629.27  5132.2 1628.62  5330.2 1629.88
  5372.6 1630.82  5386.8 1630.08  5542.3 1630.69  5683.8 1632.18  5768.6 1634.27
  5796.9 1637.93  5867.6 1641.20  5959.5 1649.83  6009.0 1651.93  6136.3 1660.31
#Mann=3,-1,0
  4604.9    0.05       0  4957.8    0.05       0  5012.0    0.05       0
Bank Sta=4957.8,5012
Exp/Cntr=0.3,0.1

Type RM Length L Ch R = 1,4141,314,314,314
BEGIN DESCRIPTION:
Mapping XS 6cc54dda
END DESCRIPTION:
XS GIS Cut Line= 3
      1626507.28      6916900.15      1626511.62      6917073.79
      1626932.65      6917651.07
#Sta/Elev= 30
  4677.6 1647.92  4745.5 1647.20  4783.4 1645.80  4845.5 1644.79  4870.3 1644.92
  4885.0 1644.26  4893.5 1642.58  4899.6 1642.26  4914.3 1639.02  4935.2 1629.47
  4949.9 1624.68  4964.5 1621.98  4970.7 1622.02  4973.0 1612.40  4974.1 1611.80
  5026.0 1611.80  5027.2 1612.40  5029.4 1623.53  5035.6 1624.90  5042.2 1625.18
  5056.5 1624.84  5071.1 1625.62  5092.0 1625.17  5165.4 1627.99  5307.5 1628.65
  5314.5 1629.02  5343.0 1628.58  5401.1 1629.22  5443.5 1628.87  5565.8 1630.05
#Mann=3,-1,0
  4677.6    0.05       0  4973.0    0.05       0  5027.2    0.05       0
Bank Sta=4973,5027.2
Exp/Cntr=0.3,0.1

Type RM Length L Ch R = 1,3827,518,518,518
BEGIN DESCRIPTION:
Spring Creek 3.0
END DESCRIPTION:
XS GIS Cut Line= 3
      1626455.01      6916937.96      1626355.00      6917388.00
      1627155.01      6918188.01
#Sta/Elev= 30
  4544.8 1644.77  4612.7 1643.40  4617.8 1642.63  4661.4 1641.06  4704.9 1640.52
  4719.0 1639.38  4739.5 1639.33  4753.6 1638.26  4831.7 1635.54  4882.9 1628.83
  4894.4 1626.43  4903.4 1623.66  4923.9 1619.68  4932.8 1619.78  4937.7 1617.03
  4938.9 1616.43  4990.8 1616.43  4991.9 1617.03  4995.6 1617.67  5009.4 1617.56
  5034.1 1622.73  5048.2 1624.30  5232.1 1627.49  5288.7 1627.34  5656.4 1630.34
  5783.6 1633.02  5854.4 1633.75  6052.3 1639.99  6080.6 1643.49  6137.2 1646.72
#Mann=3,-1,0
  4544.8    0.05       0  4937.7    0.03       0  4991.9    0.05       0
Bank Sta=4937.7,4991.9
Exp/Cntr=0.3,0.1

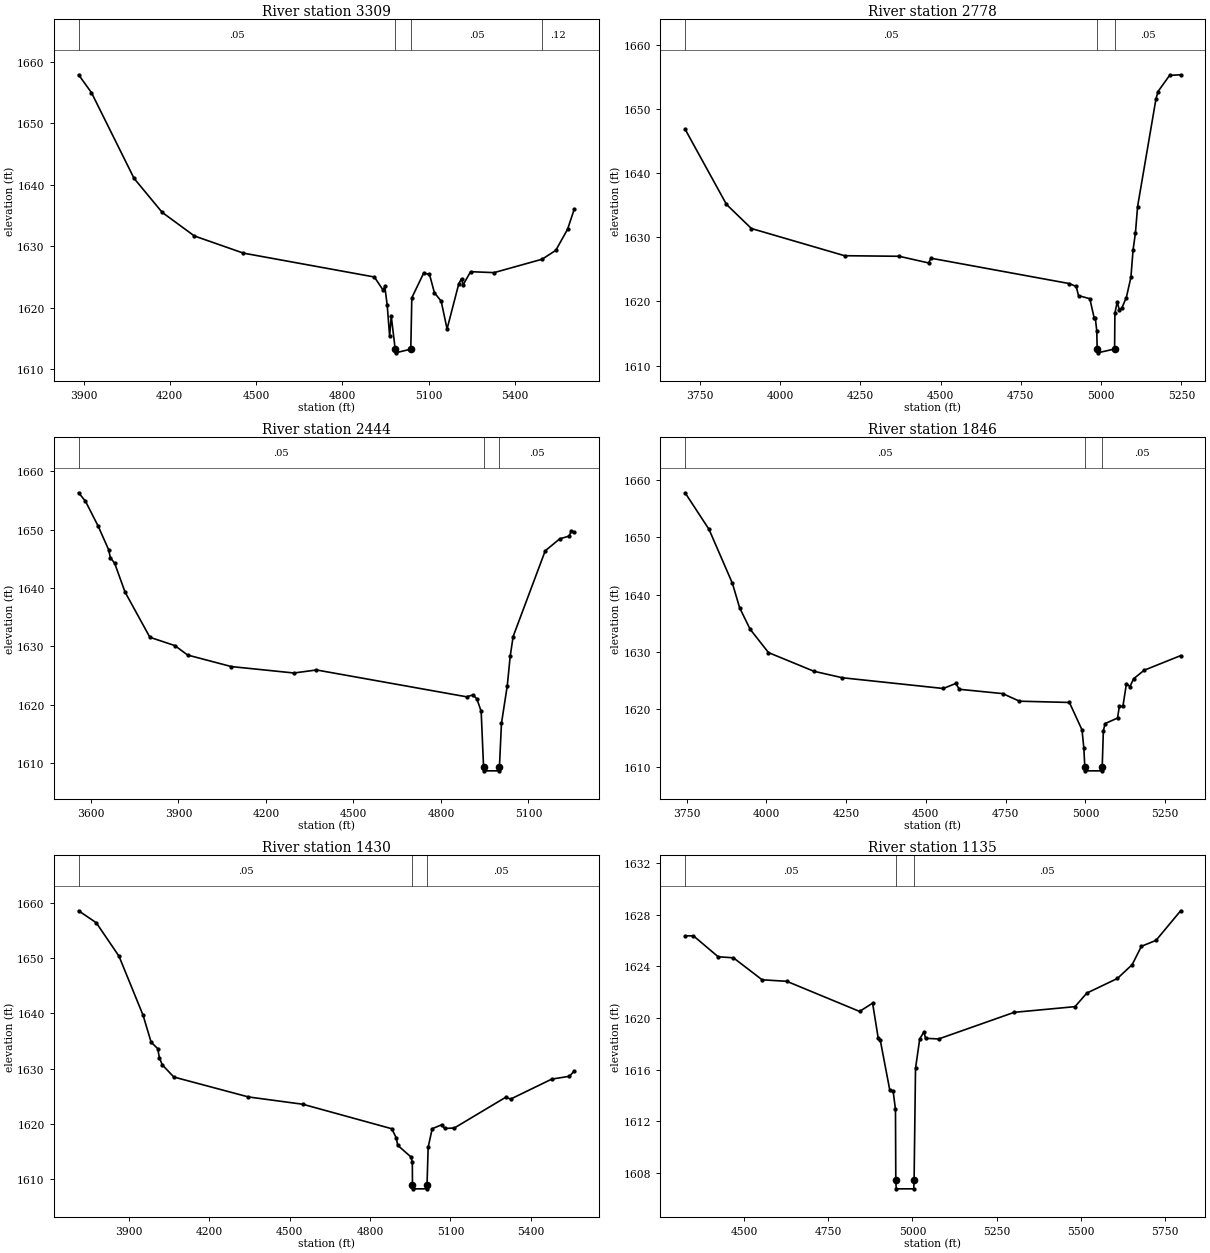
Type RM Length L Ch R = 1,3309,531,531,531
BEGIN DESCRIPTION:
Spring Creek 2.0
END DESCRIPTION:
XS GIS Cut Line= 3
      1626404.98      6916588.03      1625905.00      6917588.00
      1626029.86      6918180.59
#Sta/Elev= 30
  3883.0 1657.86  3927.7 1654.95  4075.8 1641.02  4173.7 1635.49  4285.5 1631.66
  4456.0 1628.87  4911.6 1624.99  4942.3 1622.84  4947.9 1623.46  4956.3 1620.41
  4964.7 1615.35  4970.3 1618.63  4984.1 1613.26  4985.3 1612.66  5038.3 1613.26
  5041.9 1621.61  5082.8 1625.59  5103.2 1625.45  5120.4 1622.44  5144.1 1621.05
  5164.5 1616.54  5205.4 1623.92  5214.9 1624.71  5220.0 1623.69  5246.3 1625.85
  5328.0 1625.70  5495.3 1627.88  5542.6 1629.32  5583.5 1632.73  5606.6 1635.97
#Mann=4,-1,0
  3883.0    0.05       0  4984.1    0.03       0  5038.3    0.05       0
  5495.3    0.12       0
Bank Sta=4984.1,5038.3
Exp/Cntr=0.3,0.1

Type RM Length L Ch R = 1,2778,334,334,334
BEGIN DESCRIPTION:
Mapping XS 746515bd
END DESCRIPTION:
XS GIS Cut Line= 3
      1626317.56      6916668.32      1625445.07      6917601.88
      1625270.60      6917802.53
#Sta/Elev= 30
  3704.0 1646.87  3832.9 1635.14  3910.6 1631.38  4200.8 1627.14  4370.8 1627.05
  4462.6 1626.01  4469.9 1626.75  4901.3 1622.79  4922.3 1622.34  4929.6 1620.92
  4964.8 1620.43  4978.2 1617.46  4981.8 1617.46  4986.4 1615.41  4987.7 1612.59
  4988.9 1611.99  5042.0 1612.59  5042.9 1618.15  5050.0 1619.92  5056.6 1618.74
  5064.3 1618.96  5078.5 1620.61  5092.8 1623.78  5099.4 1627.99  5107.0 1630.75
  5113.6 1634.81  5170.6 1651.52  5177.2 1652.75  5213.3 1655.27  5247.7 1655.36
#Mann=3,-1,0
  3704.0    0.05       0  4987.7    0.03       0  5042.0    0.05       0
Bank Sta=4987.7,5042
Exp/Cntr=0.3,0.1

Type RM Length L Ch R = 1,2444,598,598,598
BEGIN DESCRIPTION:
Mapping XS 02c5d69a
END DESCRIPTION:
XS GIS Cut Line= 3
      1626318.50      6916538.72      1625179.65      6917389.39
      1625169.23      6917667.21
#Sta/Elev= 30
  3557.5 1656.33  3581.0 1654.88  3624.3 1650.63  3660.2 1646.59  3666.4 1645.20
  3681.0 1644.26  3716.5 1639.33  3801.9 1631.56  3887.4 1630.14  3931.2 1628.52
  4081.3 1626.54  4296.0 1625.44  4373.2 1625.96  4888.0 1621.36  4909.9 1621.68
  4923.4 1621.00  4938.0 1618.87  4946.3 1609.27  4947.4 1608.67  4999.4 1608.67
  5000.6 1609.27  5007.6 1616.79  5027.6 1623.27  5037.6 1628.30  5047.6 1631.68
  5157.7 1646.38  5207.8 1648.45  5239.7 1648.90  5247.8 1649.83  5257.0 1649.60
#Mann=3,-1,0
  3557.5    0.05       0  4946.3    0.05       0  5000.6    0.05       0
Bank Sta=4946.3,5000.6
Exp/Cntr=0.3,0.1

Type RM Length L Ch R = 1,1846,416,416,416
BEGIN DESCRIPTION:
Mapping XS 55039acc
END DESCRIPTION:
XS GIS Cut Line= 3
      1626148.36      6916340.80      1624992.15      6916899.81
      1624870.62      6917139.39
#Sta/Elev= 30
  3745.5 1657.71  3820.5 1651.34  3893.8 1641.95  3916.4 1637.70  3949.2 1633.97
  4006.8 1629.90  4149.1 1626.65  4238.3 1625.52  4554.6 1623.65  4593.4 1624.52
  4605.3 1623.51  4740.9 1622.76  4793.3 1621.44  4949.8 1621.22  4989.4 1616.44
  4995.0 1613.31  4998.2 1609.92  4999.3 1609.32  5051.4 1609.32  5052.6 1609.92
  5056.2 1616.30  5061.8 1617.55  5100.7 1618.51  5106.3 1620.57  5117.4 1620.52
  5128.6 1624.51  5139.6 1623.98  5151.1 1625.35  5184.2 1626.83  5298.4 1629.37
#Mann=3,-1,0
  3745.5    0.05       0  4998.2    0.05       0  5052.6    0.05       0
Bank Sta=4998.2,5052.6
Exp/Cntr=0.3,0.1

Type RM Length L Ch R = 1,1430,295,295,295
BEGIN DESCRIPTION:
Mapping XS 03cf0e21
END DESCRIPTION:
XS GIS Cut Line= 4
      1626016.42      6916087.32      1624832.43      6916542.17
      1624773.81      6916779.45      1624843.89      6917109.93
#Sta/Elev= 30
  3711.7 1658.53  3777.5 1656.37  3862.4 1650.33  3952.4 1639.65  3982.5 1634.78
  4007.1 1633.63  4013.2 1632.00  4023.9 1630.71  4067.1 1628.50  4345.8 1624.90
  4548.8 1623.58  4880.9 1619.16  4897.8 1617.53  4903.2 1616.17  4952.5 1614.07
  4957.9 1613.12  4958.4 1609.00  4959.5 1608.30  5011.6 1608.30  5012.8 1609.00
  5017.0 1615.82  5032.1 1619.16  5068.4 1619.89  5078.8 1619.20  5115.0 1619.30
  5306.2 1624.83  5325.2 1624.52  5478.5 1628.12  5544.3 1628.63  5562.3 1629.57
#Mann=3,-1,0
  3711.7    0.05       0  4958.4    0.05       0  5012.8    0.05       0
Bank Sta=4958.4,5012.8
Exp/Cntr=0.3,0.1

Type RM Length L Ch R = 1,1135,212,212,212
BEGIN DESCRIPTION:
Mapping XS 42614d78
END DESCRIPTION:
XS GIS Cut Line= 4
      1625333.10      6916012.64      1624702.71      6916313.96
      1624622.96      6916700.25      1624808.30      6917032.27
#Sta/Elev= 30
  4323.9 1626.35  4348.7 1626.35  4422.3 1624.73  4467.6 1624.65  4552.8 1622.95
  4626.4 1622.83  4842.7 1620.50  4881.4 1621.14  4898.1 1618.43  4904.1 1618.29
  4932.3 1614.44  4942.5 1614.32  4949.4 1612.92  4950.4 1607.47  4951.6 1606.77
  5003.7 1606.77  5004.8 1607.47  5009.0 1616.09  5021.5 1618.37  5033.9 1618.91
  5039.0 1618.42  5077.8 1618.37  5302.4 1620.43  5483.2 1620.87  5518.4 1621.92
  5609.2 1623.05  5653.2 1624.12  5680.6 1625.54  5724.1 1626.00  5797.3 1628.29
#Mann=3,-1,0
  4323.9    0.05       0  4950.4    0.05       0  5004.8    0.05       0
Bank Sta=4950.4,5004.8
Exp/Cntr=0.3,0.1

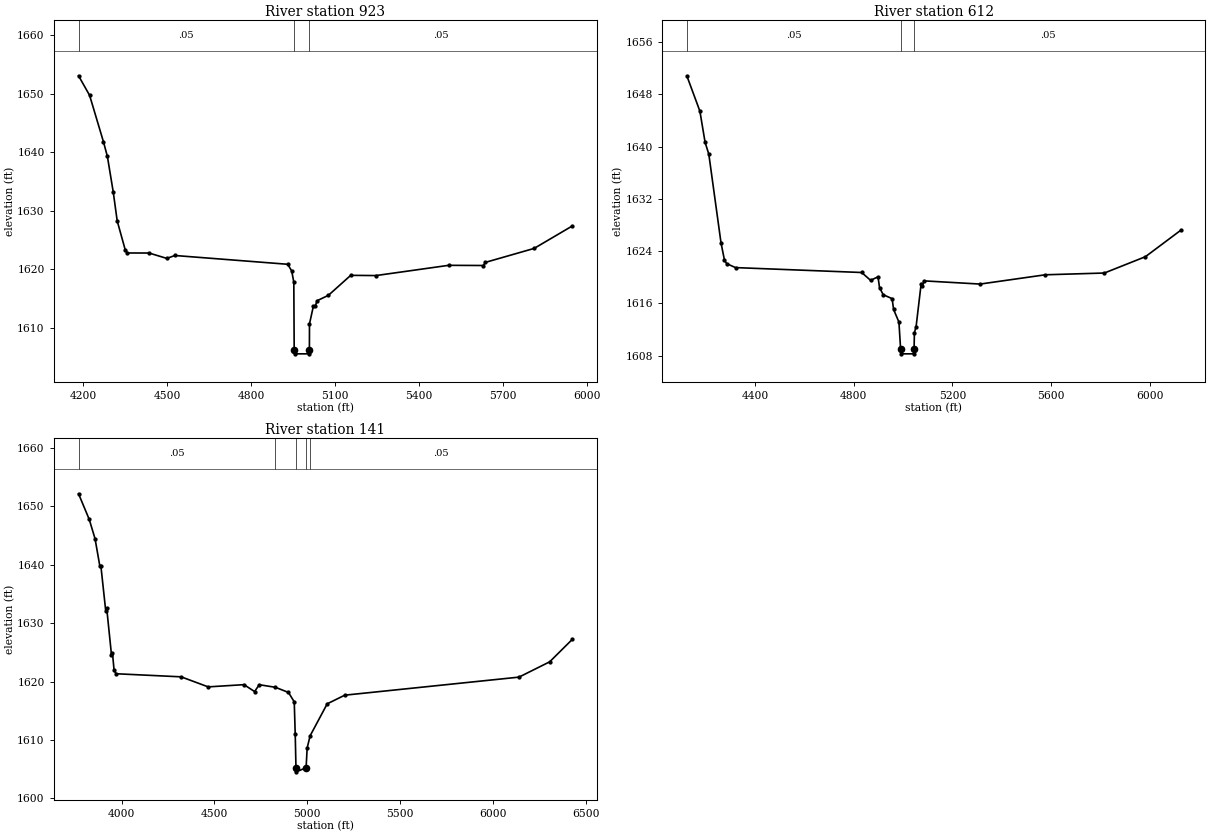
Type RM Length L Ch R = 1,923,311,311,311
BEGIN DESCRIPTION:
Mapping XS 0ee473f1
END DESCRIPTION:
XS GIS Cut Line= 4
      1625216.80      6915604.52      1624580.79      6916158.62
      1624590.43      6916707.89      1624787.06      6917024.41
#Sta/Elev= 30
  4182.6 1653.03  4222.1 1649.69  4271.4 1641.79  4285.7 1639.25  4306.5 1633.21
  4320.8 1628.23  4349.3 1623.32  4356.9 1622.76  4434.7 1622.75  4498.3 1621.83
  4526.8 1622.33  4930.3 1620.83  4944.5 1619.69  4952.1 1617.77  4953.4 1606.23
  4954.6 1605.53  5006.7 1605.53  5007.8 1606.23  5008.1 1610.65  5021.8 1613.63
  5028.3 1613.63  5035.5 1614.61  5075.5 1615.52  5155.5 1618.94  5245.5 1618.90
  5505.6 1620.65  5630.1 1620.62  5635.9 1621.14  5811.1 1623.54  5948.1 1627.39
#Mann=3,-1,0
  4182.6    0.05       0  4953.4    0.05       0  5007.8    0.05       0
Bank Sta=4953.4,5007.8
Exp/Cntr=0.3,0.1

Type RM Length L Ch R = 1,612,471,471,471
BEGIN DESCRIPTION:
Mapping XS 4ee4f4ed
END DESCRIPTION:
XS GIS Cut Line= 4
      1625100.44      6915521.22      1624353.18      6916018.09
      1624572.28      6916726.26      1624780.47      6917022.33
#Sta/Elev= 30
  4124.4 1650.85  4177.4 1645.43  4198.4 1640.67  4213.5 1638.85  4263.0 1625.26
  4276.6 1622.69  4285.6 1622.10  4321.7 1621.49  4832.7 1620.74  4868.8 1619.54
  4898.9 1620.08  4904.9 1618.44  4919.9 1617.34  4956.0 1616.74  4962.0 1615.08
  4983.6 1613.15  4990.4 1608.99  4991.6 1608.29  5043.7 1608.29  5044.9 1608.99
  5046.3 1611.52  5053.1 1612.45  5073.7 1619.05  5079.0 1618.68  5084.5 1619.46
  5312.5 1618.97  5576.5 1620.39  5815.7 1620.66  5982.1 1623.16  6125.0 1627.20
#Mann=3,-1,0
  4124.4    0.05       0  4990.4    0.03       0  5044.9    0.05       0
Bank Sta=4990.4,5044.9
Exp/Cntr=0.3,0.1

Type RM Length L Ch R = 1,141,0,0,0
BEGIN DESCRIPTION:
Spring Creek 1.0
END DESCRIPTION:
XS GIS Cut Line= 4
      1625105.88      6915424.69      1623964.07      6915816.53
      1624536.04      6916705.89      1624769.10      6917026.55
#Sta/Elev= 30
  3768.2 1652.17  3825.9 1647.77  3857.2 1644.46  3883.2 1639.73  3888.5 1639.83
  3914.5 1632.15  3919.7 1632.64  3945.7 1624.57  3951.0 1624.88  3959.4 1622.03
  3970.0 1621.35  4320.9 1620.82  4466.6 1619.10  4659.5 1619.48  4716.7 1618.30
  4741.8 1619.47  4828.5 1619.03  4899.0 1618.15  4930.3 1616.54  4935.5 1611.05
  4939.6 1605.25  4940.8 1604.55  4994.1 1605.25  4999.9 1608.64  5015.9 1610.73
  5107.9 1616.20  5202.6 1617.68  6141.0 1620.77  6306.4 1623.39  6429.2 1627.26
#Mann=5,-1,0
  3768.2    0.05       0  4828.5    0.12       0  4939.6    0.07       0
  4994.1    0.12       0  5015.9    0.05       0
Bank Sta=4939.6,4994.1
Exp/Cntr=0.3,0.1

Chan Stop Cuts=-1