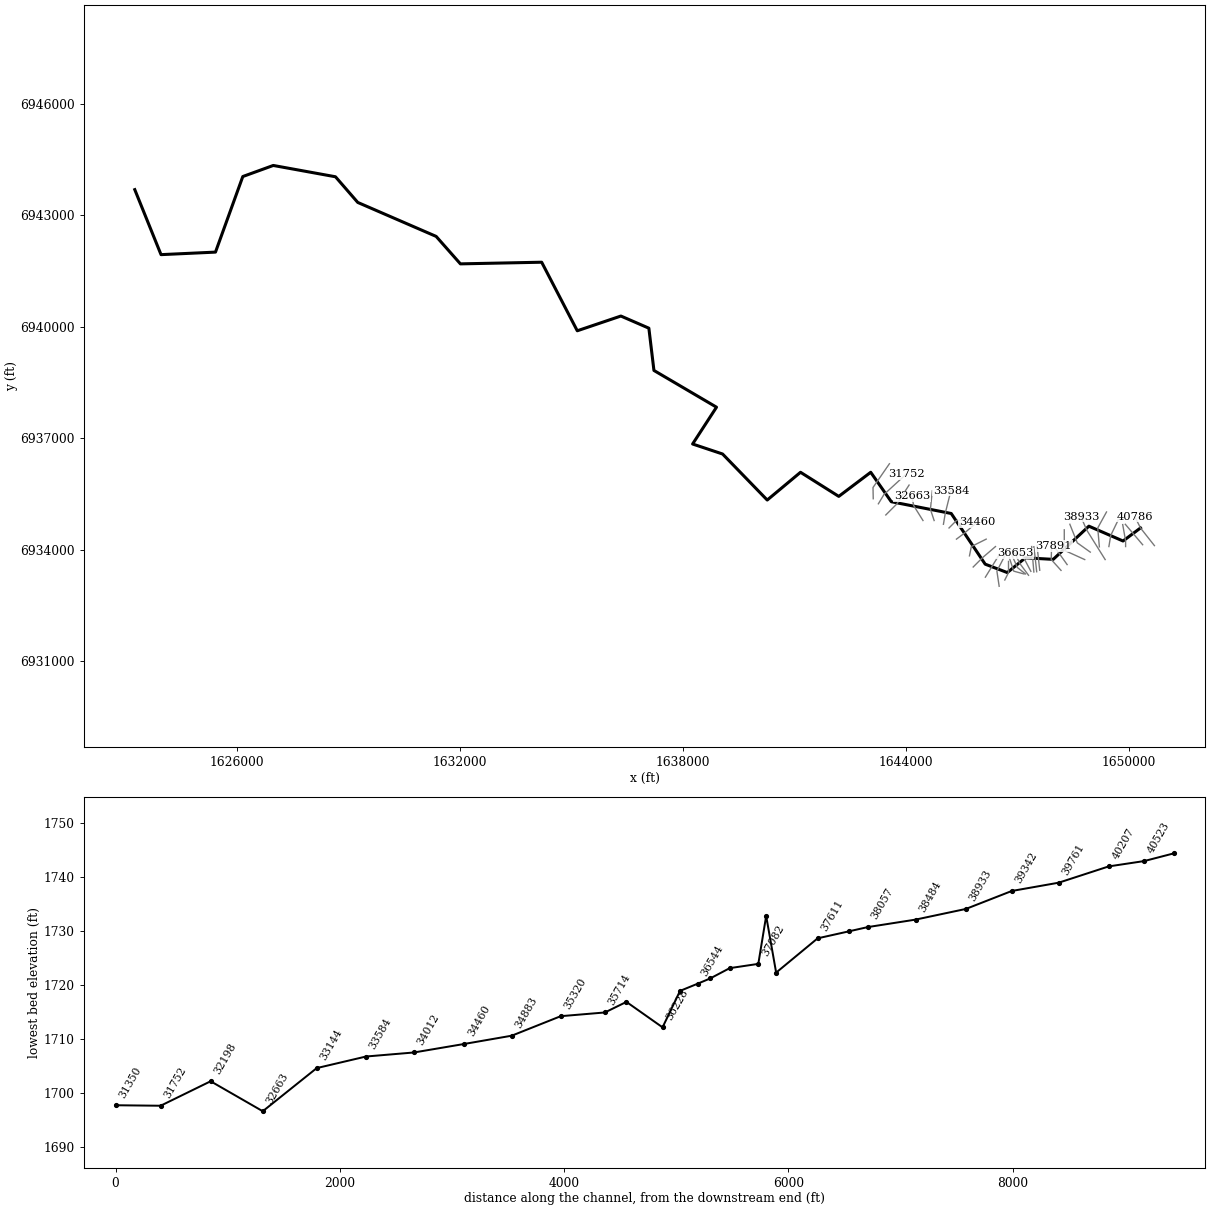
--- Threemile Creek.prj (project) ---

Proj Title=Threemile Creek Base Level Engineering
Current Plan=p01
Default Exp/Contr=0.3,0.1
English Units
Geom File=g01
Flow File=f01
Plan File=p01
BEGIN DESCRIPTION:
Threemile Creek
END DESCRIPTION:

--- Threemile Creek.p01 (plan) ---

Plan Title=Multiple Run
Short Identifier=Multiple
Geom File=g01
Flow File=f01
Subcritical Flow
K Sum by GR= 0
Std Step Tol= 0.01
Critical Tol= 0.01
Num of Std Step Trials= 20
Max Error Tol= 0.3
Flow Tol Ratio= 0.001
Split Flow NTrial= 30
Split Flow Tol= 0.02
Split Flow Ratio= 0.02
Log Output Level= 0
Friction Slope Method= 1
Unsteady Friction Slope Method= 2
Unsteady Bridges Friction Slope Method= 1
Parabolic Critical Depth
Global Vel Dist=  1 , 1 , 1
Global Log Level= 0
CheckData=True
Encroach Param= -1, 0, 0, 0
BEGIN DESCRIPTION:
Multiple Run
END DESCRIPTION:

--- Threemile Creek.f01 (steady flow) ---

Flow Title=Multiple
Number of Profiles=7
Profile Names=10-year,25-year,50-year,1pct_min,100-year,1pct_plu,500-year
River Rch & RM= Threemile Creek,Reach-1,40786
     206     281     342     208     414     827     614
River Rch & RM= Threemile Creek,Reach-1,40523
     256     353     433     264     528    1053     793
River Rch & RM= Threemile Creek,Reach-1,36228
     508     727     914     570    1138    2271    1790
River Rch & RM= Threemile Creek,Reach-1,32198
     594     855    1078     675    1348    2689    2133
River Rch & RM= Threemile Creek,Reach-1,27616
     667     963    1217     763    1523    3038    2418
River Rch & RM= Threemile Creek,Reach-1,20214
     698    1010    1278     802    1601    3195    2548
River Rch & RM= Threemile Creek,Reach-1,16566
    1010    1486    1902    1207    2408    4805    3914
River Rch & RM= Threemile Creek,Reach-1,12035
    1081    1595    2046    1301    2596    5180    4238
River Rch & RM= Threemile Creek,Reach-1,8058
    1155    1709    2196    1399    2791    5569    4570
River Rch & RM= Threemile Creek,Reach-1,3543
    1163    1720    2210    1407    2808    5603    4596
Boundary for River Rch & Prof#=Threemile Creek,Reach-1,1
Up Type=0
Dn Type=3
Dn Slope=0.003
Boundary for River Rch & Prof#=Threemile Creek,Reach-1,2
Up Type=0
Dn Type=3
Dn Slope=0.003
Boundary for River Rch & Prof#=Threemile Creek,Reach-1,3
Up Type=0
Dn Type=3
Dn Slope=0.003
Boundary for River Rch & Prof#=Threemile Creek,Reach-1,4
Up Type=0
Dn Type=3
Dn Slope=0.003
Boundary for River Rch & Prof#=Threemile Creek,Reach-1,5
Up Type=0
Dn Type=3
Dn Slope=0.003
Boundary for River Rch & Prof#=Threemile Creek,Reach-1,6
Up Type=0
Dn Type=3
Dn Slope=0.003
Boundary for River Rch & Prof#=Threemile Creek,Reach-1,7
Up Type=0
Dn Type=3
Dn Slope=0.003

--- Threemile Creek.g01 (geometry) ---

Geom Title=Existing Conditions

River Reach=Threemile Creek,Reach-1
Reach XY= 30
      1650305.00      6934588.00      1649834.97      6934237.39
      1648916.87      6934636.27      1647957.43      6933743.52
      1647210.89      6933786.04      1646723.20      6933388.12
      1646127.86      6933614.43      1645214.70      6934977.26
      1643602.70      6935293.83      1643049.32      6936086.03
      1642189.84      6935437.52      1641160.86      6936085.94
      1640265.55      6935339.10      1639064.79      6936577.48
      1638258.46      6936846.47      1638901.25      6937836.45
      1637218.62      6938824.78      1637082.14      6939961.53
      1636329.92      6940288.20      1635156.46      6939891.54
      1634199.10      6941735.77      1632013.44      6941691.41
      1631361.06      6942429.86      1629252.56      6943343.52
      1628653.37      6944034.06      1626980.08      6944338.20
      1626160.47      6944040.44      1625425.66      6942007.43
      1623961.03      6941939.62      1623255.00      6943688.00

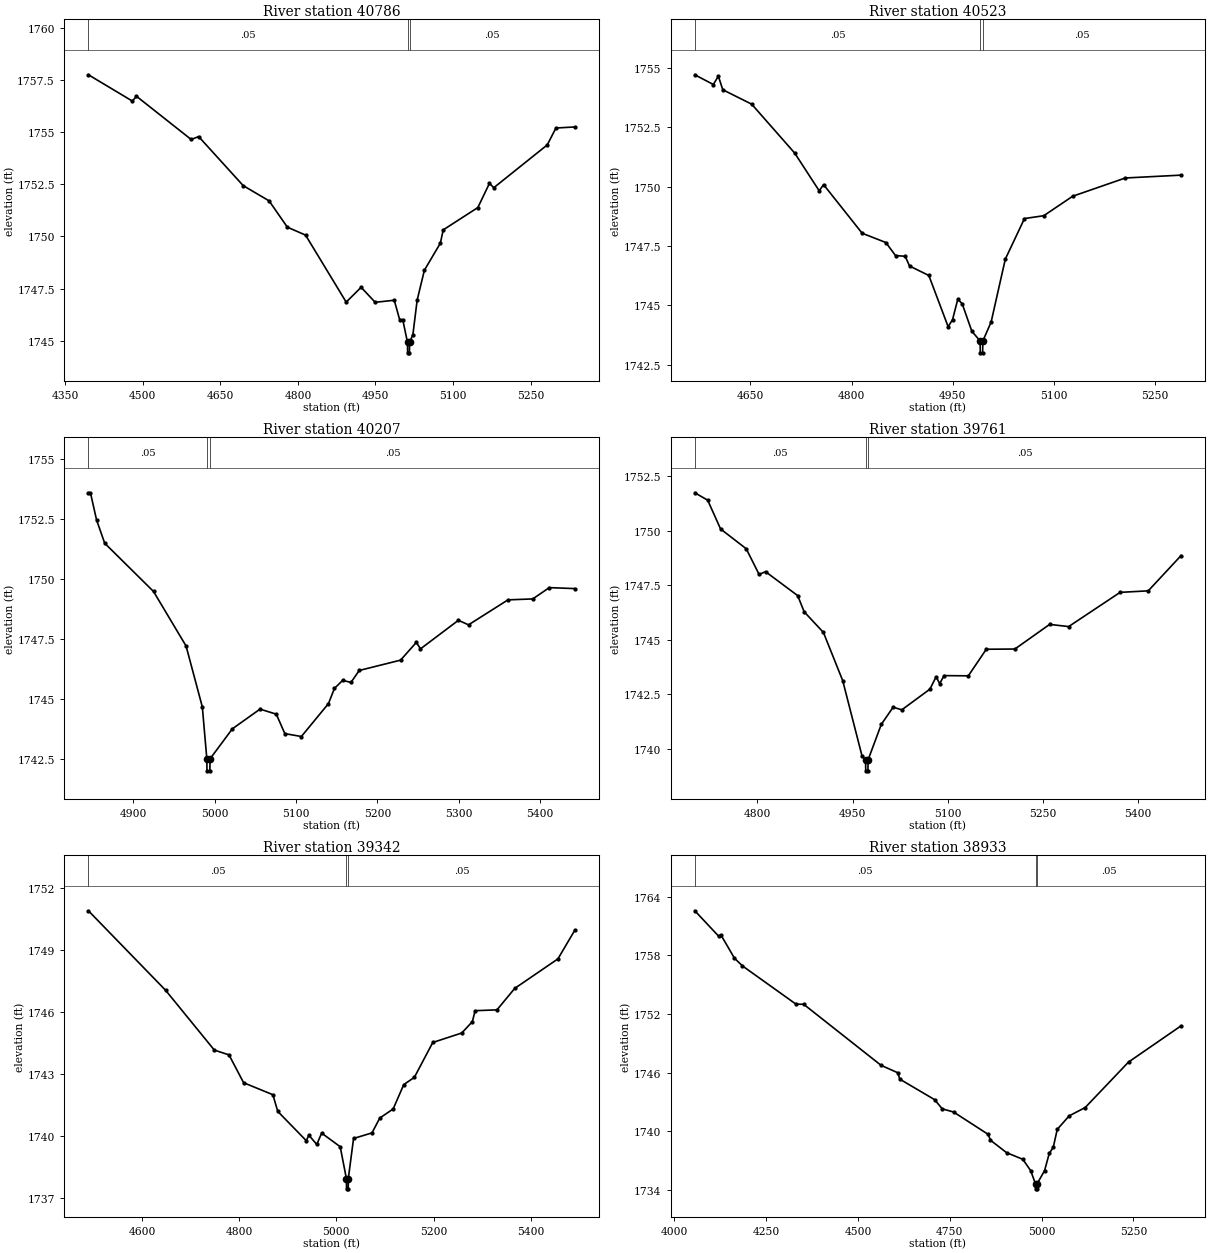
Type RM Length L Ch R = 1,40786,263,263,263
BEGIN DESCRIPTION:
Threemile Creek 78.0
END DESCRIPTION:
XS GIS Cut Line= 3
      1650680.01      6934112.99      1650305.00      6934588.00
      1650155.00      6934887.99
#Sta/Elev= 30
  4394.8 1757.74  4479.8 1756.48  4487.8 1756.71  4593.6 1754.64  4608.0 1754.78
  4694.2 1752.43  4744.3 1751.70  4779.6 1750.44  4814.8 1750.06  4893.4 1746.85
  4922.3 1747.56  4949.5 1746.84  4986.4 1746.94  4996.8 1746.01  5002.8 1746.01
  5012.0 1744.92  5012.2 1744.42  5015.7 1744.42  5016.0 1744.92  5022.4 1745.29
  5030.7 1746.95  5044.7 1748.38  5075.5 1749.67  5081.1 1750.31  5148.1 1751.38
  5170.5 1752.54  5178.9 1752.33  5282.3 1754.38  5299.1 1755.19  5335.4 1755.24
#Mann=3,-1,0
  4394.8    0.05       0  5012.0    0.03       0  5016.0    0.05       0
Bank Sta=5012,5016
Exp/Cntr=0.3,0.1

Type RM Length L Ch R = 1,40523,316,316,316
BEGIN DESCRIPTION:
Mapping XS 0e097248
END DESCRIPTION:
XS GIS Cut Line= 2
      1650363.13      6934137.11      1649896.97      6934686.62
#Sta/Elev= 30
  4567.8 1754.72  4595.2 1754.31  4602.7 1754.66  4609.2 1754.09  4652.1 1753.48
  4715.8 1751.42  4752.1 1749.83  4758.6 1750.09  4815.8 1748.04  4850.9 1747.65
  4865.2 1747.10  4879.5 1747.07  4886.0 1746.66  4914.6 1746.26  4943.2 1744.10
  4949.7 1744.40  4957.5 1745.26  4964.0 1745.07  4978.3 1743.91  4990.6 1743.50
  4990.8 1743.00  4994.3 1743.00  4994.6 1743.50  5006.9 1744.30  5027.9 1746.95
  5056.3 1748.66  5084.9 1748.78  5127.7 1749.60  5205.7 1750.37  5288.4 1750.49
#Mann=3,-1,0
  4567.8    0.05       0  4990.6    0.03       0  4994.6    0.05       0
Bank Sta=4990.6,4994.6
Exp/Cntr=0.3,0.1

Type RM Length L Ch R = 1,40207,446,446,446
BEGIN DESCRIPTION:
Threemile Creek 77.0
END DESCRIPTION:
XS GIS Cut Line= 3
      1649905.00      6934088.05      1649905.00      6934238.00
      1649826.68      6934678.74
#Sta/Elev= 30
  4844.9 1753.59  4847.4 1753.59  4854.9 1752.46  4864.9 1751.49  4924.9 1749.48
  4964.9 1747.21  4984.9 1744.67  4990.4 1742.51  4990.6 1742.01  4994.1 1742.01
  4994.4 1742.51  5021.8 1743.76  5055.8 1744.58  5075.8 1744.37  5086.3 1743.56
  5106.6 1743.44  5139.9 1744.81  5147.2 1745.44  5157.4 1745.78  5167.5 1745.69
  5177.7 1746.19  5228.5 1746.62  5247.9 1747.36  5253.0 1747.09  5299.6 1748.28
  5312.0 1748.09  5360.5 1749.13  5391.0 1749.17  5411.3 1749.64  5442.5 1749.60
#Mann=3,-1,0
  4844.9    0.05       0  4990.4    0.03       0  4994.4    0.05       0
Bank Sta=4990.4,4994.4
Exp/Cntr=0.3,0.1

Type RM Length L Ch R = 1,39761,419,419,419
BEGIN DESCRIPTION:
Threemile Creek 76.0
END DESCRIPTION:
XS GIS Cut Line= 3
      1649455.00      6934087.97      1649505.00      6934388.00
      1649706.05      6934804.67
#Sta/Elev= 30
  4701.3 1751.75  4721.6 1751.41  4741.9 1750.09  4782.4 1749.18  4802.7 1748.00
  4812.8 1748.13  4863.5 1747.03  4873.7 1746.29  4904.1 1745.34  4934.5 1743.13
  4964.9 1739.68  4970.5 1739.49  4970.8 1738.99  4974.3 1738.99  4974.5 1739.49
  4995.3 1741.12  5014.0 1741.91  5027.7 1741.79  5072.1 1742.74  5081.8 1743.31
  5087.4 1742.99  5094.3 1743.36  5132.6 1743.35  5160.9 1744.57  5206.0 1744.58
  5260.8 1745.71  5290.8 1745.61  5371.9 1747.18  5416.3 1747.25  5468.1 1748.87
#Mann=3,-1,0
  4701.3    0.05       0  4970.5    0.03       0  4974.5    0.05       0
Bank Sta=4970.5,4974.5
Exp/Cntr=0.3,0.1

Type RM Length L Ch R = 1,39342,409,409,409
BEGIN DESCRIPTION:
Threemile Creek 75.0
END DESCRIPTION:
XS GIS Cut Line= 3
      1649199.07      6934079.81      1649155.00      6934588.00
      1649390.88      6935018.29
#Sta/Elev= 30
  4489.7 1750.92  4648.5 1747.07  4748.9 1744.17  4779.0 1743.94  4809.1 1742.59
  4869.3 1742.01  4879.4 1741.20  4938.2 1739.78  4943.3 1740.05  4959.7 1739.60
  4969.7 1740.15  5007.9 1739.49  5020.6 1737.95  5020.9 1737.45  5024.4 1737.45
  5024.6 1737.95  5035.4 1739.89  5073.3 1740.16  5089.4 1740.88  5116.9 1741.32
  5138.7 1742.50  5160.5 1742.85  5198.4 1744.54  5258.1 1745.00  5279.9 1745.55
  5285.6 1746.08  5330.5 1746.12  5367.1 1747.16  5456.0 1748.59  5490.5 1749.97
#Mann=3,-1,0
  4489.7    0.05       0  5020.6    0.03       0  5024.6    0.05       0
Bank Sta=5020.6,5024.6
Exp/Cntr=0.3,0.1

Type RM Length L Ch R = 1,38933,449,449,449
BEGIN DESCRIPTION:
Threemile Creek 74.0
END DESCRIPTION:
XS GIS Cut Line= 3
      1649354.97      6933738.04      1648855.00      6934538.00
      1648705.02      6934887.96
#Sta/Elev= 30
  4056.0 1762.57  4121.4 1759.95  4127.3 1760.08  4163.9 1757.72  4185.7 1756.93
  4331.3 1753.02  4352.5 1753.00  4563.0 1746.76  4608.4 1746.00  4614.3 1745.34
  4708.7 1743.25  4729.9 1742.30  4760.6 1741.98  4854.9 1739.69  4860.8 1739.10
  4905.0 1737.82  4949.2 1737.14  4970.5 1735.98  4983.7 1734.62  4984.0 1734.12
  4987.6 1734.12  4987.8 1734.62  5008.4 1735.99  5021.1 1737.75  5032.0 1738.37
  5042.9 1740.21  5075.5 1741.59  5119.0 1742.44  5236.9 1747.09  5380.1 1750.80
#Mann=3,-1,0
  4056.0    0.05       0  4983.7    0.03       0  4987.8    0.05       0
Bank Sta=4983.7,4987.8
Exp/Cntr=0.3,0.1

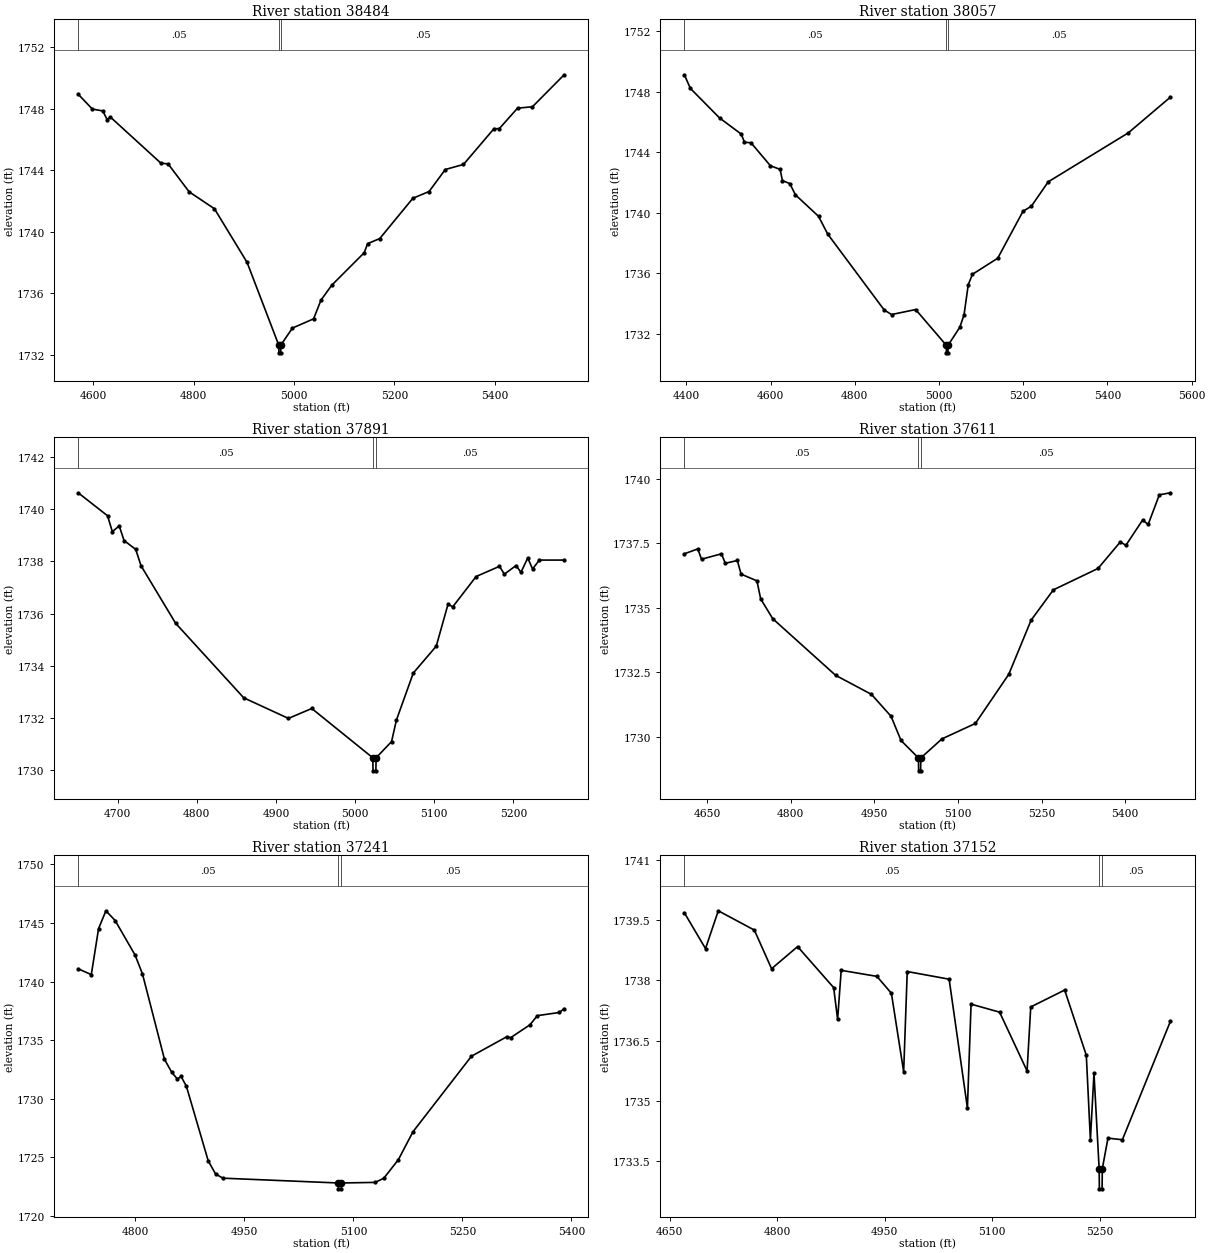
Type RM Length L Ch R = 1,38484,427,427,427
BEGIN DESCRIPTION:
Threemile Creek 73.0
END DESCRIPTION:
XS GIS Cut Line= 3
      1648955.00      6933938.00      1648605.00      6934188.00
      1648405.01      6934687.97
#Sta/Elev= 30
  4569.8 1748.96  4598.1 1747.99  4619.0 1747.87  4627.6 1747.30  4633.7 1747.48
  4734.5 1744.48  4749.2 1744.42  4791.0 1742.61  4841.4 1741.51  4906.5 1738.02
  4969.6 1732.64  4969.9 1732.14  4973.5 1732.14  4973.7 1732.64  4996.8 1733.75
  5039.0 1734.35  5053.8 1735.57  5075.3 1736.54  5139.9 1738.65  5146.7 1739.24
  5170.9 1739.57  5236.9 1742.19  5269.2 1742.63  5301.5 1744.06  5337.8 1744.39
  5398.4 1746.71  5409.2 1746.72  5445.5 1748.05  5475.2 1748.14  5538.4 1750.22
#Mann=3,-1,0
  4569.8    0.05       0  4969.6    0.03       0  4973.7    0.05       0
Bank Sta=4969.6,4973.7
Exp/Cntr=0.3,0.1

Type RM Length L Ch R = 1,38057,166,166,166
BEGIN DESCRIPTION:
Threemile Creek 72.0
END DESCRIPTION:
XS GIS Cut Line= 3
      1648805.03      6933737.98      1648255.00      6933988.00
      1648255.00      6934538.01
#Sta/Elev= 30
  4395.2 1749.12  4409.5 1748.22  4478.7 1746.27  4530.3 1745.20  4538.0 1744.66
  4553.4 1744.63  4599.6 1743.11  4622.6 1742.87  4628.1 1742.13  4645.7 1741.93
  4658.9 1741.19  4713.8 1739.77  4735.8 1738.59  4869.8 1733.58  4887.3 1733.28
  4944.5 1733.61  5017.3 1731.25  5017.6 1730.75  5021.2 1730.75  5021.5 1731.25
  5049.4 1732.44  5059.4 1733.26  5069.4 1735.25  5079.4 1735.94  5139.4 1737.00
  5199.4 1740.10  5219.4 1740.44  5259.4 1742.05  5449.4 1745.28  5549.4 1747.64
#Mann=3,-1,0
  4395.2    0.05       0  5017.3    0.03       0  5021.5    0.05       0
Bank Sta=5017.3,5021.5
Exp/Cntr=0.3,0.1

Type RM Length L Ch R = 1,37891,280,280,280
BEGIN DESCRIPTION:
Mapping XS a59297ea
END DESCRIPTION:
XS GIS Cut Line= 2
      1648331.88      6933603.26      1647975.19      6934103.15
#Sta/Elev= 30
  4650.0 1740.63  4687.1 1739.75  4693.2 1739.14  4701.9 1739.36  4708.0 1738.80
  4722.7 1738.46  4729.5 1737.83  4773.1 1735.63  4859.2 1732.77  4915.7 1731.98
  4945.2 1732.36  5022.3 1730.47  5022.6 1729.97  5026.2 1729.97  5026.5 1730.47
  5046.0 1731.09  5052.2 1731.92  5073.5 1733.72  5102.5 1734.75  5117.3 1736.35
  5123.4 1736.26  5152.9 1737.42  5182.4 1737.81  5188.6 1737.51  5203.3 1737.84
  5209.5 1737.58  5218.1 1738.13  5224.2 1737.71  5232.8 1738.05  5264.1 1738.05
#Mann=3,-1,0
  4650.0    0.05       0  5022.3    0.05       0  5026.5    0.05       0
Bank Sta=5022.3,5026.5
Exp/Cntr=0.3,0.1

Type RM Length L Ch R = 1,37611,370,370,370
BEGIN DESCRIPTION:
Threemile Creek 71.0
END DESCRIPTION:
XS GIS Cut Line= 3
      1648167.80      6933447.03      1647905.00      6933738.00
      1647915.21      6934217.81
#Sta/Elev= 30
  4608.9 1737.10  4632.9 1737.29  4639.7 1736.89  4675.5 1737.10  4682.3 1736.73
  4703.9 1736.84  4710.7 1736.31  4739.1 1736.05  4745.8 1735.35  4767.4 1734.58
  4880.3 1732.38  4944.6 1731.64  4979.7 1730.79  4997.6 1729.85  5028.9 1729.17
  5029.2 1728.67  5032.8 1728.67  5033.1 1729.17  5071.0 1729.91  5131.0 1730.51
  5191.0 1732.42  5231.0 1734.52  5271.0 1735.70  5351.1 1736.53  5391.1 1737.56
  5401.1 1737.43  5431.1 1738.41  5441.1 1738.24  5461.1 1739.39  5480.9 1739.47
#Mann=3,-1,0
  4608.9    0.05       0  5028.9    0.05       0  5033.1    0.05       0
Bank Sta=5028.9,5033.1
Exp/Cntr=0.3,0.1

Type RM Length L Ch R = 1,37241,89,89,89
BEGIN DESCRIPTION:
Mapping XS e2c2c362
END DESCRIPTION:
XS GIS Cut Line= 2
      1647595.34      6933450.04      1647521.73      6934114.68
#Sta/Elev= 30
  4721.2 1741.09  4739.3 1740.59  4749.3 1744.52  4759.4 1746.04  4772.1 1745.21
  4799.6 1742.25  4809.7 1740.65  4839.9 1733.38  4849.9 1732.26  4857.7 1731.68
  4862.8 1731.90  4870.1 1731.07  4900.2 1724.69  4910.3 1723.58  4920.4 1723.22
  5079.1 1722.81  5079.4 1722.31  5083.2 1722.31  5083.5 1722.81  5129.8 1722.86
  5141.7 1723.21  5161.8 1724.80  5182.0 1727.19  5262.4 1733.63  5311.2 1735.30
  5316.3 1735.21  5342.9 1736.31  5353.0 1737.09  5383.2 1737.36  5389.9 1737.69
#Mann=3,-1,0
  4721.2    0.05       0  5079.1    0.03       0  5083.5    0.05       0
Bank Sta=5079.1,5083.5
Exp/Cntr=0.3,0.1

Type RM Length L Ch R = 1,37152,70,70,70
BEGIN DESCRIPTION:
Threemile Creek 70.0
END DESCRIPTION:
XS GIS Cut Line= 3
      1647512.87      6933411.00      1647478.15      6933734.34
      1647437.09      6934084.44
#Sta/Elev= 30
  4670.5 1739.68  4700.0 1738.79  4717.8 1739.73  4768.1 1739.25  4792.1 1738.29
  4828.4 1738.84  4878.7 1737.82  4884.2 1737.03  4889.2 1738.25  4939.0 1738.10
  4959.2 1737.68  4976.3 1735.73  4981.3 1738.22  5039.7 1738.03  5065.2 1734.83
  5070.3 1737.41  5110.1 1737.21  5148.4 1735.75  5153.5 1737.34  5200.8 1737.76
  5231.0 1736.14  5236.7 1734.04  5241.7 1735.69  5248.9 1733.32  5249.2 1732.82
  5253.0 1732.82  5253.3 1733.32  5261.2 1734.08  5281.3 1734.04  5348.2 1736.98
#Mann=3,-1,0
  4670.5    0.05       0  5248.9    0.03       0  5253.3    0.05       0
Bank Sta=5248.9,5253.3
Exp/Cntr=0.3,0.1

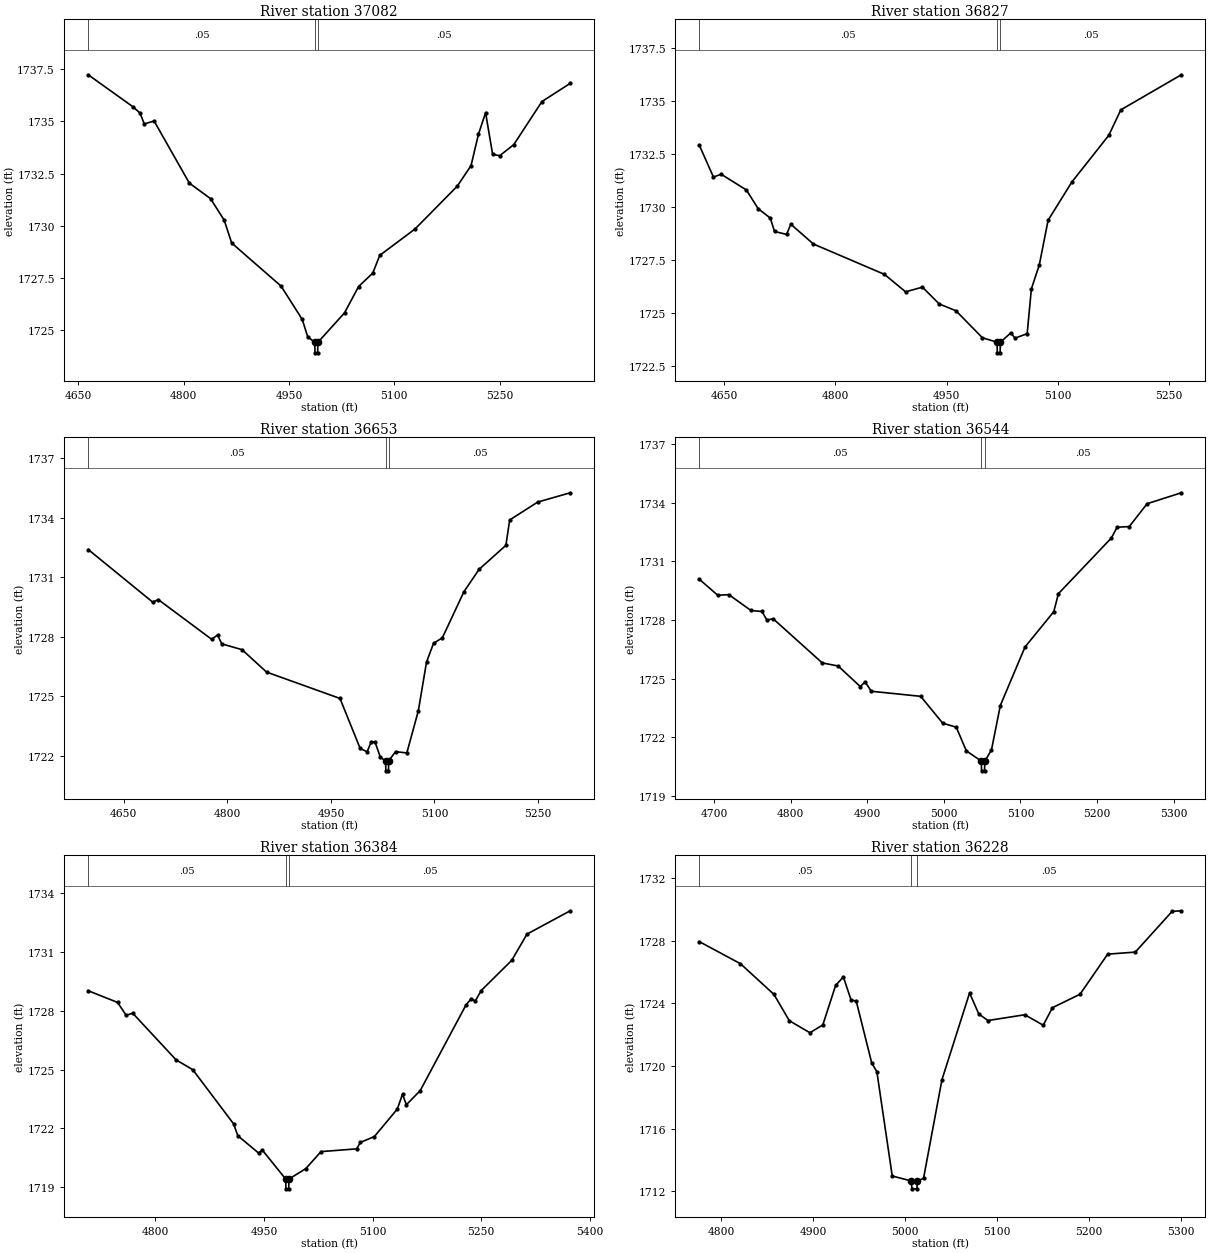
Type RM Length L Ch R = 1,37082,255,255,255
BEGIN DESCRIPTION:
Mapping XS 00dbed5e
END DESCRIPTION:
XS GIS Cut Line= 2
      1647436.91      6933404.52      1647378.32      6934088.11
#Sta/Elev= 30
  4664.3 1737.22  4728.0 1735.69  4738.1 1735.39  4744.1 1734.87  4758.1 1735.01
  4808.3 1732.04  4838.4 1731.30  4857.9 1730.27  4868.5 1729.18  4938.8 1727.12
  4968.9 1725.53  4976.7 1724.70  4986.8 1724.43  4987.1 1723.93  4990.9 1723.93
  4991.2 1724.43  5029.1 1725.84  5049.2 1727.10  5069.3 1727.74  5079.3 1728.59
  5129.5 1729.85  5189.7 1731.90  5209.2 1732.88  5219.8 1734.38  5229.9 1735.41
  5239.9 1733.42  5249.9 1733.35  5270.0 1733.88  5310.1 1735.94  5350.4 1736.81
#Mann=3,-1,0
  4664.3    0.05       0  4986.8    0.03       0  4991.2    0.05       0
Bank Sta=4986.8,4991.2
Exp/Cntr=0.3,0.1

Type RM Length L Ch R = 1,36827,174,174,174
BEGIN DESCRIPTION:
Mapping XS 21bfb3a6
END DESCRIPTION:
XS GIS Cut Line= 2
      1647356.64      6933421.81      1647052.82      6933996.89
#Sta/Elev= 30
  4616.3 1732.91  4635.4 1731.41  4645.9 1731.54  4679.9 1730.80  4695.8 1729.92
  4712.1 1729.48  4717.8 1728.85  4734.1 1728.71  4739.8 1729.19  4770.3 1728.26
  4866.2 1726.83  4894.7 1726.01  4917.4 1726.23  4940.0 1725.44  4962.6 1725.12
  4998.3 1723.85  5018.1 1723.64  5018.4 1723.14  5022.2 1723.14  5022.6 1723.64
  5036.7 1724.08  5042.3 1723.83  5058.7 1724.04  5064.4 1726.15  5075.1 1727.28
  5087.0 1729.38  5119.1 1731.18  5168.8 1733.37  5185.1 1734.57  5266.7 1736.22
#Mann=3,-1,0
  4616.3    0.05       0  5018.1    0.03       0  5022.6    0.05       0
Bank Sta=5018.1,5022.6
Exp/Cntr=0.3,0.1

Type RM Length L Ch R = 1,36653,109,109,109
BEGIN DESCRIPTION:
Threemile Creek 69.0
END DESCRIPTION:
XS GIS Cut Line= 3
      1647293.69      6933315.49      1647055.00      6933638.00
      1646931.27      6933907.96
#Sta/Elev= 30
  4598.5 1732.39  4691.8 1729.74  4700.2 1729.86  4777.4 1727.86  4785.8 1728.08
  4792.0 1727.63  4821.3 1727.34  4856.8 1726.21  4963.2 1724.88  4992.4 1722.36
  5002.5 1722.19  5008.5 1722.70  5014.0 1722.68  5021.7 1721.91  5029.2 1721.73
  5029.6 1721.23  5033.4 1721.23  5033.7 1721.73  5043.7 1722.20  5060.0 1722.13
  5076.7 1724.26  5088.5 1726.71  5098.7 1727.66  5111.5 1727.94  5142.7 1730.26
  5164.7 1731.39  5203.5 1732.60  5209.0 1733.88  5249.5 1734.78  5296.7 1735.25
#Mann=3,-1,0
  4598.5    0.05       0  5029.2    0.03       0  5033.7    0.05       0
Bank Sta=5029.2,5033.7
Exp/Cntr=0.3,0.1

Type RM Length L Ch R = 1,36544,160,160,160
BEGIN DESCRIPTION:
Mapping XS c12786ef
END DESCRIPTION:
XS GIS Cut Line= 3
      1647213.42      6933351.58      1646994.70      6933523.42
      1646852.21      6933844.69
#Sta/Elev= 30
  4680.6 1730.08  4704.7 1729.26  4719.2 1729.29  4748.1 1728.48  4762.5 1728.43
  4768.9 1727.99  4777.0 1728.06  4841.2 1725.80  4862.0 1725.64  4890.9 1724.59
  4897.2 1724.83  4905.3 1724.35  4969.8 1724.09  4998.5 1722.72  5016.3 1722.51
  5029.4 1721.30  5049.0 1720.78  5049.3 1720.28  5053.2 1720.28  5053.5 1720.78
  5062.2 1721.34  5073.8 1723.62  5106.0 1726.61  5143.6 1728.42  5149.7 1729.34
  5218.9 1732.19  5226.3 1732.74  5242.2 1732.77  5265.5 1733.94  5310.2 1734.50
#Mann=3,-1,0
  4680.6    0.05       0  5049.0    0.03       0  5053.5    0.05       0
Bank Sta=5049,5053.5
Exp/Cntr=0.3,0.1

Type RM Length L Ch R = 1,36384,156,156,156
BEGIN DESCRIPTION:
Mapping XS 552b0bde
END DESCRIPTION:
XS GIS Cut Line= 3
      1647174.29      6933350.24      1646896.55      6933426.18
      1646777.77      6933784.68
#Sta/Elev= 30
  4707.3 1729.03  4748.0 1728.43  4759.6 1727.78  4768.8 1727.88  4828.7 1725.50
  4851.7 1725.00  4908.0 1722.24  4913.9 1721.63  4942.5 1720.75  4947.7 1720.90
  4980.0 1719.42  4980.3 1718.92  4984.2 1718.92  4984.5 1719.42  5007.7 1719.95
  5028.8 1720.82  5077.9 1720.96  5083.2 1721.29  5102.5 1721.59  5134.1 1722.99
  5141.3 1723.75  5146.6 1723.21  5165.7 1723.93  5228.9 1728.30  5236.4 1728.63
  5241.7 1728.50  5250.0 1729.04  5292.1 1730.58  5313.2 1731.92  5372.9 1733.11
#Mann=3,-1,0
  4707.3    0.05       0  4980.0    0.03       0  4984.5    0.05       0
Bank Sta=4980,4984.5
Exp/Cntr=0.3,0.1

Type RM Length L Ch R = 1,36228,322,322,322
BEGIN DESCRIPTION:
Threemile Creek 68.0
END DESCRIPTION:
XS GIS Cut Line= 3
      1646655.00      6933188.01      1646755.00      6933388.00
      1646755.00      6933688.00
#Sta/Elev= 30
  4776.4 1727.95  4821.1 1726.54  4857.5 1724.58  4874.2 1722.90  4896.6 1722.13
  4910.6 1722.63  4924.5 1725.15  4932.9 1725.70  4941.3 1724.22  4946.9 1724.15
  4963.7 1720.20  4969.3 1719.64  4986.0 1712.98  5006.8 1712.66  5007.3 1712.16
  5012.8 1712.16  5013.3 1712.66  5020.0 1712.83  5040.0 1719.13  5070.0 1724.67
  5080.0 1723.33  5090.0 1722.91  5130.0 1723.28  5150.0 1722.61  5160.0 1723.73
  5190.0 1724.59  5220.0 1727.15  5250.0 1727.28  5290.0 1729.88  5300.0 1729.92
#Mann=3,-1,0
  4776.4    0.05       0  5006.8    0.05       0  5013.3    0.05       0
Bank Sta=5006.8,5013.3
Exp/Cntr=0.3,0.1

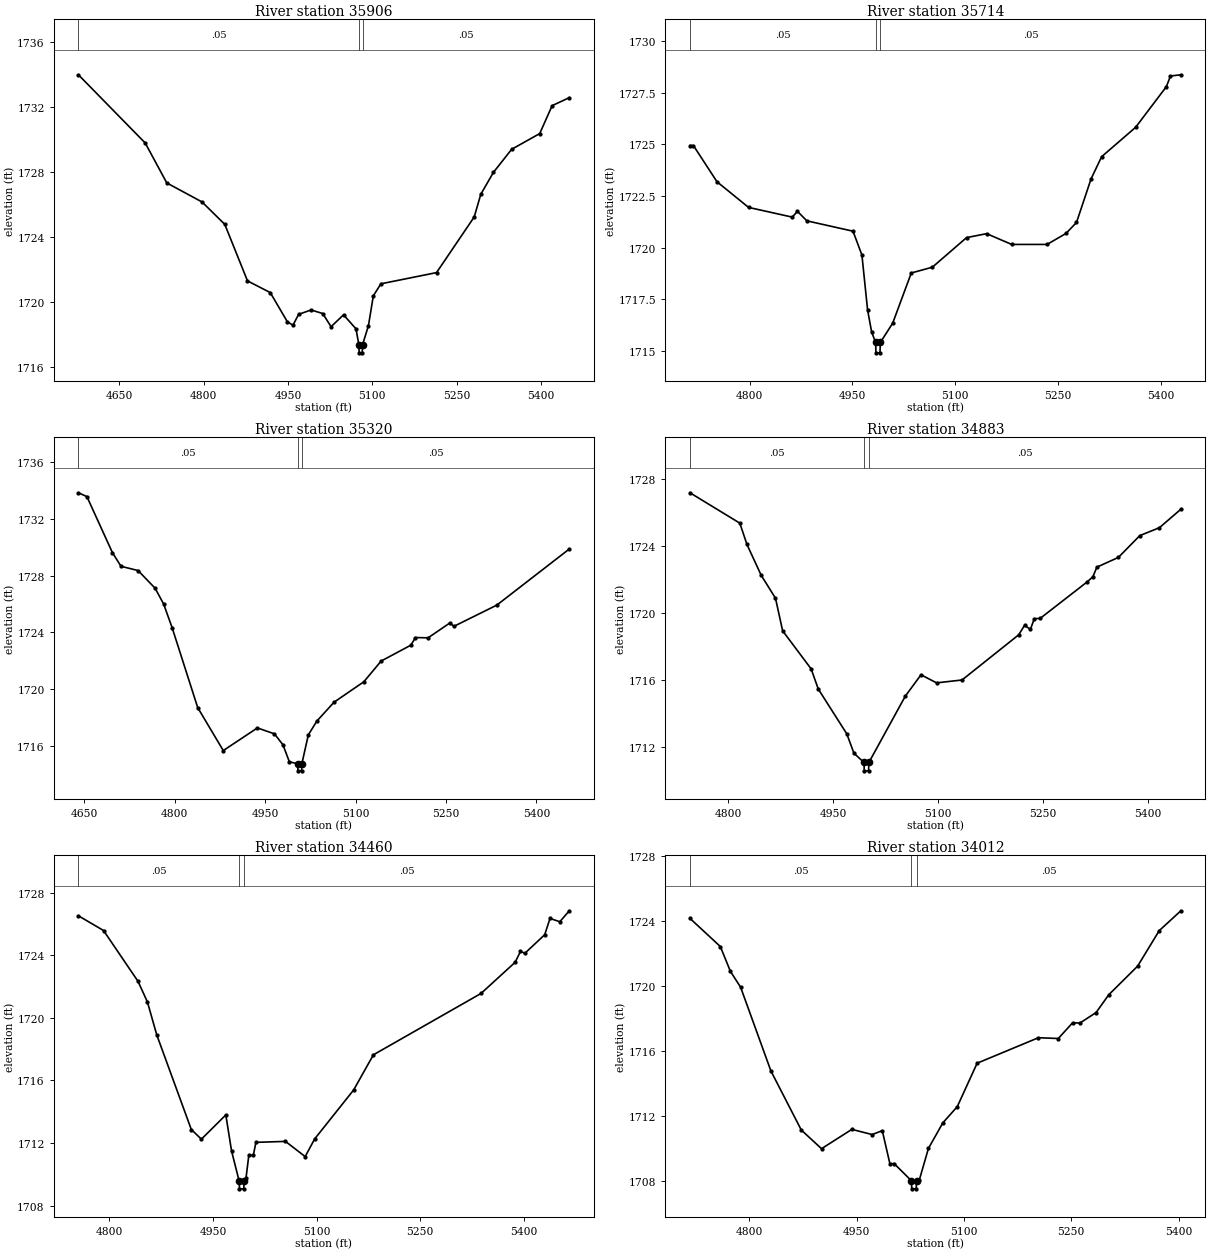
Type RM Length L Ch R = 1,35906,192,192,192
BEGIN DESCRIPTION:
Threemile Creek 67.0
END DESCRIPTION:
XS GIS Cut Line= 3
      1646503.75      6933020.41      1646442.99      6933426.18
      1646655.01      6933838.01
#Sta/Elev= 30
  4576.9 1734.00  4695.8 1729.80  4734.2 1727.34  4796.9 1726.17  4837.4 1724.79
  4877.8 1721.31  4918.3 1720.59  4948.6 1718.80  4958.7 1718.58  4968.8 1719.25
  4991.0 1719.52  5011.7 1719.30  5026.5 1718.49  5048.7 1719.22  5070.8 1718.36
  5076.0 1717.38  5076.5 1716.88  5082.0 1716.88  5082.5 1717.38  5093.0 1718.55
  5101.7 1720.39  5115.2 1721.13  5214.2 1721.82  5281.3 1725.25  5292.9 1726.64
  5315.4 1727.99  5347.8 1729.41  5397.8 1730.38  5419.9 1732.10  5450.4 1732.59
#Mann=3,-1,0
  4576.9    0.05       0  5076.0    0.03       0  5082.5    0.05       0
Bank Sta=5076,5082.5
Exp/Cntr=0.3,0.1

Type RM Length L Ch R = 1,35714,394,394,394
BEGIN DESCRIPTION:
Mapping XS f879980a
END DESCRIPTION:
XS GIS Cut Line= 2
      1646132.49      6933264.47      1646509.06      6933874.26
#Sta/Elev= 30
  4712.9 1724.94  4717.9 1724.94  4752.3 1723.19  4798.4 1721.95  4862.2 1721.48
  4869.8 1721.76  4883.5 1721.30  4950.9 1720.80  4963.9 1719.65  4972.2 1716.99
  4978.1 1715.93  4983.9 1715.42  4984.4 1714.92  4990.3 1714.92  4990.8 1715.42
  5008.8 1716.35  5036.0 1718.78  5066.8 1719.06  5116.7 1720.49  5146.0 1720.68
  5182.6 1720.16  5234.2 1720.16  5261.8 1720.69  5277.2 1721.22  5298.5 1723.33
  5313.9 1724.40  5363.5 1725.82  5408.5 1727.79  5414.4 1728.30  5429.6 1728.36
#Mann=3,-1,0
  4712.9    0.05       0  4983.9    0.03       0  4990.8    0.05       0
Bank Sta=4983.9,4990.8
Exp/Cntr=0.3,0.1

Type RM Length L Ch R = 1,35320,437,437,437
BEGIN DESCRIPTION:
Threemile Creek 66.0
END DESCRIPTION:
XS GIS Cut Line= 3
      1645805.01      6933538.01      1646055.00      6933788.00
      1646404.99      6934087.99
#Sta/Elev= 30
  4640.2 1733.86  4654.3 1733.59  4696.7 1729.63  4710.9 1728.67  4739.2 1728.37
  4767.5 1727.12  4781.6 1726.01  4795.7 1724.34  4838.2 1718.69  4880.6 1715.66
  4937.2 1717.26  4965.5 1716.84  4979.6 1716.07  4990.2 1714.87  5004.0 1714.73
  5004.5 1714.23  5010.5 1714.23  5011.0 1714.73  5021.7 1716.77  5036.0 1717.75
  5064.5 1719.08  5113.9 1720.52  5142.5 1721.98  5191.8 1723.10  5199.5 1723.64
  5220.4 1723.62  5256.6 1724.67  5263.2 1724.43  5334.5 1725.93  5454.7 1729.89
#Mann=3,-1,0
  4640.2    0.05       0  5004.0    0.03       0  5011.0    0.05       0
Bank Sta=5004,5011
Exp/Cntr=0.3,0.1

Type RM Length L Ch R = 1,34883,423,423,423
BEGIN DESCRIPTION:
Threemile Creek 65.0
END DESCRIPTION:
XS GIS Cut Line= 3
      1645705.01      6933838.04      1645755.00      6934088.00
      1646154.98      6934287.99
#Sta/Elev= 30
  4745.0 1727.17  4816.3 1725.36  4826.5 1724.09  4846.9 1722.25  4867.3 1720.89
  4877.5 1718.95  4918.3 1716.68  4928.5 1715.48  4969.3 1712.81  4979.5 1711.66
  4993.8 1711.11  4994.3 1710.61  5000.4 1710.61  5000.9 1711.11  5053.0 1715.06
  5075.4 1716.33  5097.7 1715.85  5134.1 1716.02  5215.1 1718.71  5223.5 1719.27
  5231.9 1719.04  5237.5 1719.67  5245.9 1719.69  5313.0 1721.86  5321.3 1722.17
  5326.9 1722.74  5357.7 1723.32  5388.4 1724.62  5416.4 1725.09  5447.1 1726.19
#Mann=3,-1,0
  4745.0    0.05       0  4993.8    0.03       0  5000.9    0.05       0
Bank Sta=4993.8,5000.9
Exp/Cntr=0.3,0.1

Type RM Length L Ch R = 1,34460,448,448,448
BEGIN DESCRIPTION:
Threemile Creek 64.0
END DESCRIPTION:
XS GIS Cut Line= 3
      1645355.02      6934288.02      1645555.00      6934438.00
      1645904.96      6934737.97
#Sta/Elev= 30
  4755.0 1726.52  4791.4 1725.58  4841.4 1722.33  4855.0 1721.01  4868.5 1718.91
  4918.5 1712.87  4933.1 1712.25  4968.5 1713.80  4976.8 1711.50  4987.8 1709.58
  4988.3 1709.08  4994.5 1709.08  4995.0 1709.58  4997.7 1709.75  5001.8 1711.22
  5008.3 1711.22  5012.1 1712.05  5054.9 1712.11  5083.4 1711.14  5097.2 1712.27
  5153.7 1715.40  5182.2 1717.64  5338.1 1721.56  5387.5 1723.55  5395.2 1724.24
  5401.7 1724.13  5430.3 1725.31  5438.0 1726.35  5452.2 1726.14  5465.9 1726.84
#Mann=3,-1,0
  4755.0    0.05       0  4987.8    0.03       0  4995.0    0.05       0
Bank Sta=4987.8,4995
Exp/Cntr=0.3,0.1

Type RM Length L Ch R = 1,34012,428,428,428
BEGIN DESCRIPTION:
Threemile Creek 63.0
END DESCRIPTION:
XS GIS Cut Line= 3
      1645155.03      6934588.03      1645355.00      6934788.00
      1645754.99      6934838.00
#Sta/Elev= 30
  4717.2 1724.14  4759.6 1722.41  4773.7 1720.88  4787.9 1719.91  4830.3 1714.75
  4872.7 1711.12  4901.0 1709.97  4943.4 1711.16  4971.7 1710.84  4985.9 1711.08
  4996.5 1709.05  5002.5 1709.05  5026.6 1708.00  5027.1 1707.50  5033.3 1707.50
  5033.8 1708.00  5037.8 1708.07  5050.4 1709.99  5070.5 1711.56  5090.7 1712.56
  5118.4 1715.23  5204.1 1716.80  5231.8 1716.75  5251.9 1717.72  5262.0 1717.70
  5284.7 1718.35  5302.3 1719.44  5342.6 1721.20  5372.9 1723.39  5403.1 1724.61
#Mann=3,-1,0
  4717.2    0.05       0  5026.6    0.03       0  5033.8    0.05       0
Bank Sta=5026.6,5033.8
Exp/Cntr=0.3,0.1

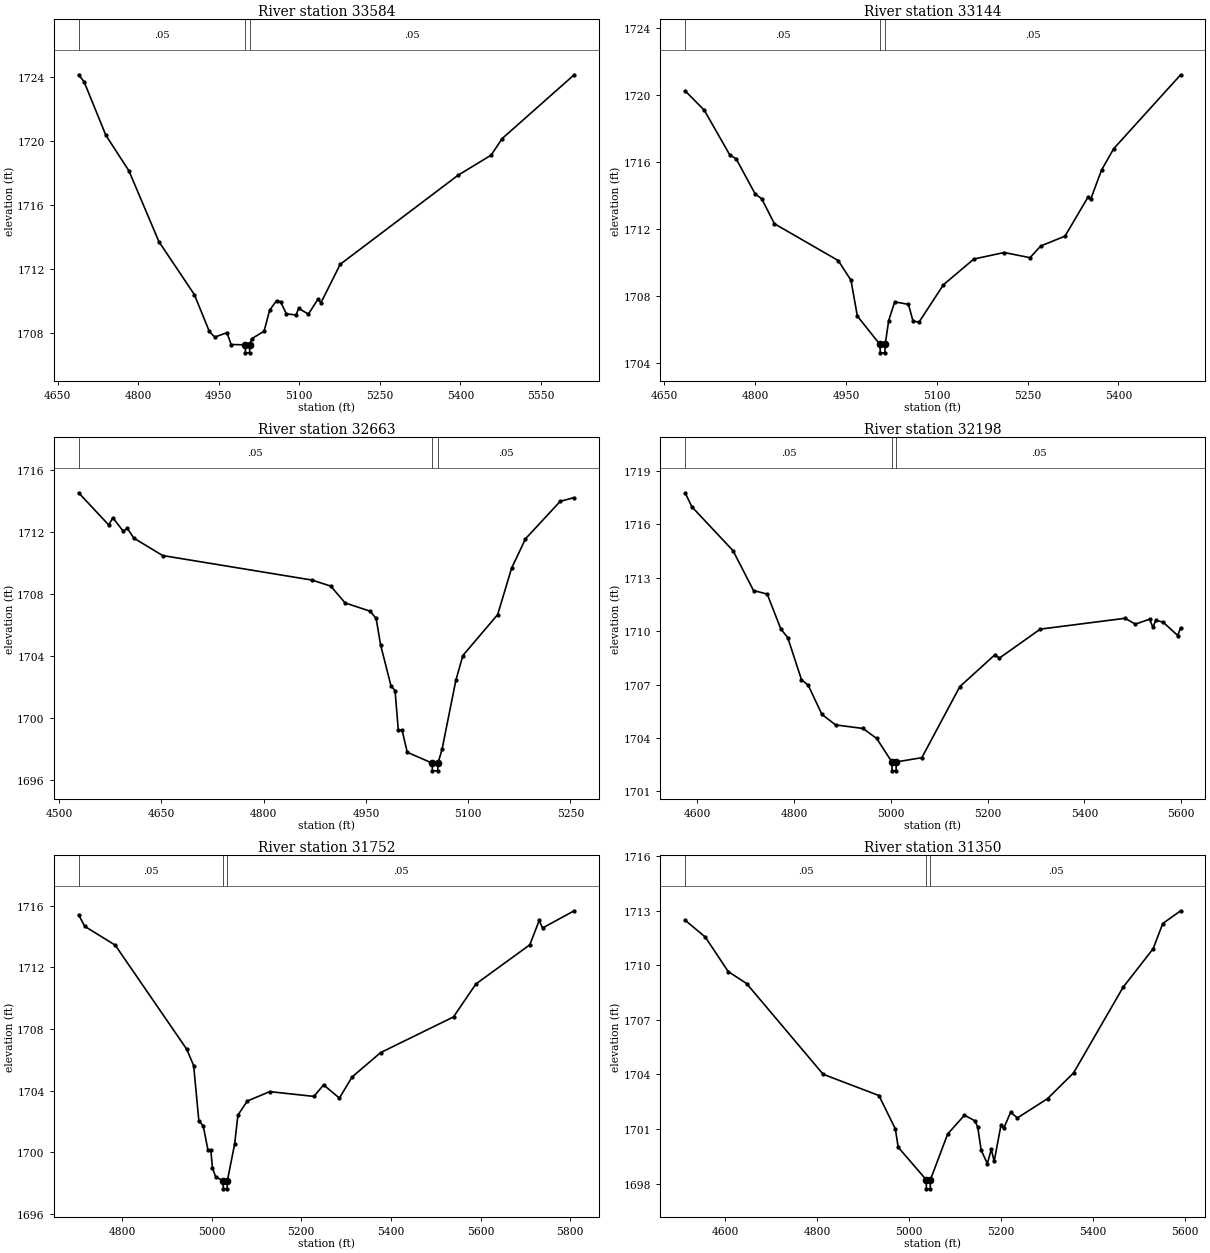
Type RM Length L Ch R = 1,33584,440,440,440
BEGIN DESCRIPTION:
Threemile Creek 62.0
END DESCRIPTION:
XS GIS Cut Line= 3
      1645005.01      6934688.05      1645055.00      6934988.00
      1645205.01      6935588.04
#Sta/Elev= 30
  4689.2 1724.11  4699.3 1723.68  4739.8 1720.34  4782.9 1718.11  4838.7 1713.69
  4904.6 1710.39  4932.5 1708.09  4942.6 1707.73  4965.4 1708.01  4973.0 1707.27
  4999.3 1707.25  4999.8 1706.75  5007.4 1706.75  5007.9 1707.25  5011.3 1707.63
  5034.5 1708.10  5044.8 1709.41  5057.7 1710.01  5065.4 1709.93  5075.8 1709.19
  5093.8 1709.11  5098.9 1709.52  5117.0 1709.17  5135.0 1710.11  5140.2 1709.87
  5176.3 1712.28  5395.3 1717.83  5457.1 1719.09  5477.8 1720.13  5611.8 1724.11
#Mann=3,-1,0
  4689.2    0.05       0  4999.3    0.03       0  5007.9    0.05       0
Bank Sta=4999.3,5007.9
Exp/Cntr=0.3,0.1

Type RM Length L Ch R = 1,33144,481,481,481
BEGIN DESCRIPTION:
Threemile Creek 61.0
END DESCRIPTION:
XS GIS Cut Line= 3
      1644755.01      6934787.96      1644655.00      6935088.00
      1644705.00      6935588.04
#Sta/Elev= 30
  4684.1 1720.27  4715.8 1719.11  4757.9 1716.44  4768.5 1716.20  4800.1 1714.09
  4810.6 1713.82  4831.7 1712.32  4937.1 1710.12  4958.2 1708.94  4968.7 1706.80
  5006.1 1705.10  5006.6 1704.60  5014.2 1704.60  5014.7 1705.10  5020.5 1706.53
  5030.5 1707.65  5053.1 1707.50  5060.7 1706.50  5070.7 1706.44  5110.9 1708.67
  5161.2 1710.21  5211.4 1710.60  5254.1 1710.29  5271.7 1710.99  5311.9 1711.58
  5349.6 1713.90  5354.6 1713.82  5372.2 1715.53  5392.3 1716.81  5502.9 1721.23
#Mann=3,-1,0
  4684.1    0.05       0  5006.1    0.05       0  5014.7    0.05       0
Bank Sta=5006.1,5014.7
Exp/Cntr=0.3,0.1

Type RM Length L Ch R = 1,32663,465,465,465
BEGIN DESCRIPTION:
Threemile Creek 60.0
END DESCRIPTION:
XS GIS Cut Line= 3
      1644455.00      6934787.99      1644205.00      6935188.00
      1644154.99      6935438.04
#Sta/Elev= 30
  4528.7 1714.54  4572.9 1712.46  4578.8 1712.93  4594.2 1712.06  4600.1 1712.25
  4609.5 1711.62  4651.9 1710.49  4870.7 1708.91  4898.4 1708.52  4919.6 1707.43
  4956.2 1706.90  4965.0 1706.43  4971.5 1704.73  4986.8 1702.08  4992.7 1701.78
  4997.5 1699.23  5003.0 1699.23  5010.6 1697.80  5047.0 1697.10  5047.5 1696.60
  5055.2 1696.60  5055.7 1697.10  5061.6 1697.98  5082.0 1702.46  5092.2 1704.04
  5143.2 1706.68  5163.6 1709.67  5184.0 1711.57  5235.0 1713.99  5255.4 1714.23
#Mann=3,-1,0
  4528.7    0.05       0  5047.0    0.03       0  5055.7    0.05       0
Bank Sta=5047,5055.7
Exp/Cntr=0.3,0.1

Type RM Length L Ch R = 1,32198,446,446,446
BEGIN DESCRIPTION:
Threemile Creek 59.0
END DESCRIPTION:
XS GIS Cut Line= 3
      1643455.00      6934938.00      1643755.00      6935238.00
      1644080.70      6935741.82
#Sta/Elev= 30
  4574.8 1717.78  4588.9 1716.99  4673.8 1714.53  4716.2 1712.29  4744.5 1712.09
  4772.8 1710.12  4786.9 1709.65  4815.2 1707.29  4829.4 1706.96  4857.6 1705.33
  4885.9 1704.74  4942.5 1704.54  4970.8 1703.98  5002.1 1702.66  5002.6 1702.16
  5010.8 1702.16  5011.3 1702.66  5064.1 1702.90  5142.6 1706.89  5215.1 1708.68
  5224.3 1708.49  5308.8 1710.12  5484.3 1710.73  5505.4 1710.40  5534.9 1710.68
  5541.7 1710.22  5547.6 1710.62  5562.8 1710.51  5593.1 1709.76  5599.0 1710.20
#Mann=3,-1,0
  4574.8    0.05       0  5002.1    0.03       0  5011.3    0.05       0
Bank Sta=5002.1,5011.3
Exp/Cntr=0.3,0.1

Type RM Length L Ch R = 1,31752,402,402,402
BEGIN DESCRIPTION:
Threemile Creek 58.0
END DESCRIPTION:
XS GIS Cut Line= 3
      1643255.00      6935238.00      1643405.00      6935488.00
      1644005.01      6936038.01
#Sta/Elev= 30
  4703.4 1715.41  4717.0 1714.66  4785.0 1713.44  4944.4 1706.69  4960.0 1705.62
  4971.6 1702.03  4981.3 1701.71  4992.0 1700.13  4998.3 1700.13  5002.0 1698.97
  5008.8 1698.42  5025.8 1698.12  5026.3 1697.62  5034.5 1697.62  5035.0 1698.12
  5051.4 1700.52  5058.8 1702.41  5079.7 1703.32  5129.7 1703.93  5228.3 1703.62
  5249.9 1704.37  5285.1 1703.51  5313.4 1704.88  5376.9 1706.46  5539.7 1708.78
  5589.7 1710.92  5709.9 1713.46  5730.9 1715.04  5738.3 1714.55  5808.9 1715.67
#Mann=3,-1,0
  4703.4    0.05       0  5025.8    0.03       0  5035.0    0.05       0
Bank Sta=5025.8,5035
Exp/Cntr=0.3,0.1

Type RM Length L Ch R = 1,31350,463,463,463
BEGIN DESCRIPTION:
Mapping XS 964b1815
END DESCRIPTION:
XS GIS Cut Line= 3
      1643117.08      6935374.25      1643110.65      6935676.44
      1643552.11      6936315.05
#Sta/Elev= 30
  4512.4 1712.48  4556.2 1711.56  4606.2 1709.66  4646.2 1709.00  4812.9 1704.01
  4934.3 1702.84  4970.1 1701.00  4976.2 1700.00  5037.2 1698.21  5037.7 1697.71
  5045.9 1697.71  5046.4 1698.21  5084.0 1700.73  5120.5 1701.76  5143.2 1701.45
  5149.3 1701.11  5156.9 1699.83  5170.2 1699.10  5179.0 1699.88  5185.1 1699.22
  5199.9 1701.21  5206.0 1701.04  5220.9 1701.92  5235.8 1701.61  5301.3 1702.67
  5358.1 1704.09  5465.6 1708.79  5531.1 1710.91  5552.1 1712.30  5591.0 1713.00
#Mann=3,-1,0
  4512.4    0.05       0  5037.2    0.03       0  5046.4    0.05       0
Bank Sta=5037.2,5046.4
Exp/Cntr=0.3,0.1