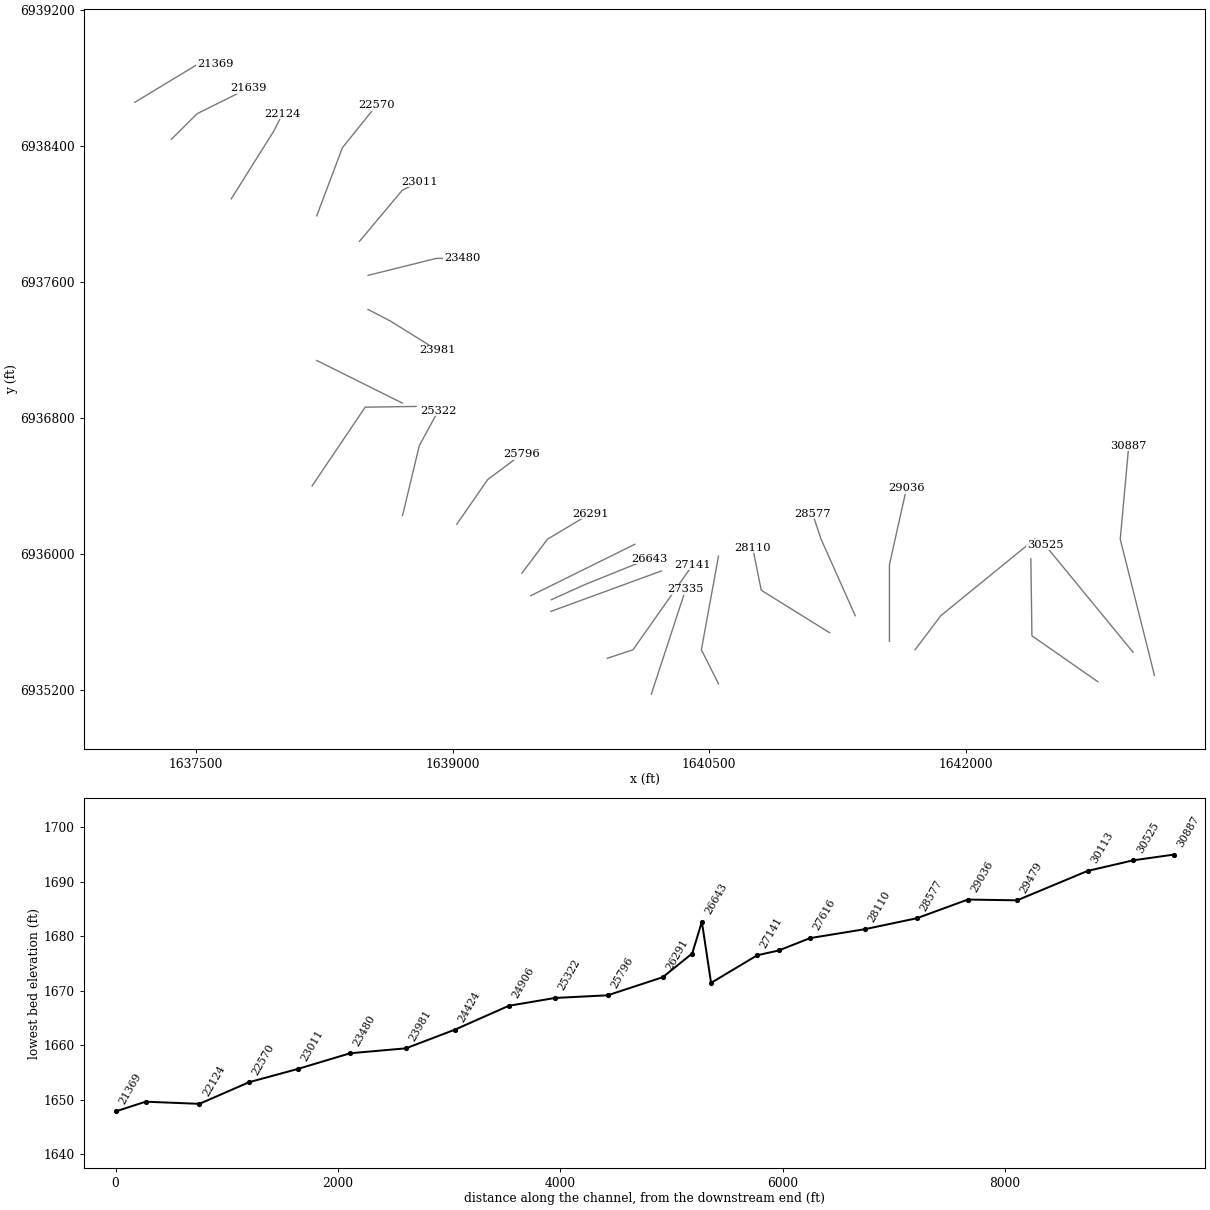
HEC-RAS study Threemile Creek.prj: Threemile Creek Base Level Engineering

--- Threemile Creek.g01 (geometry) --- (continued)

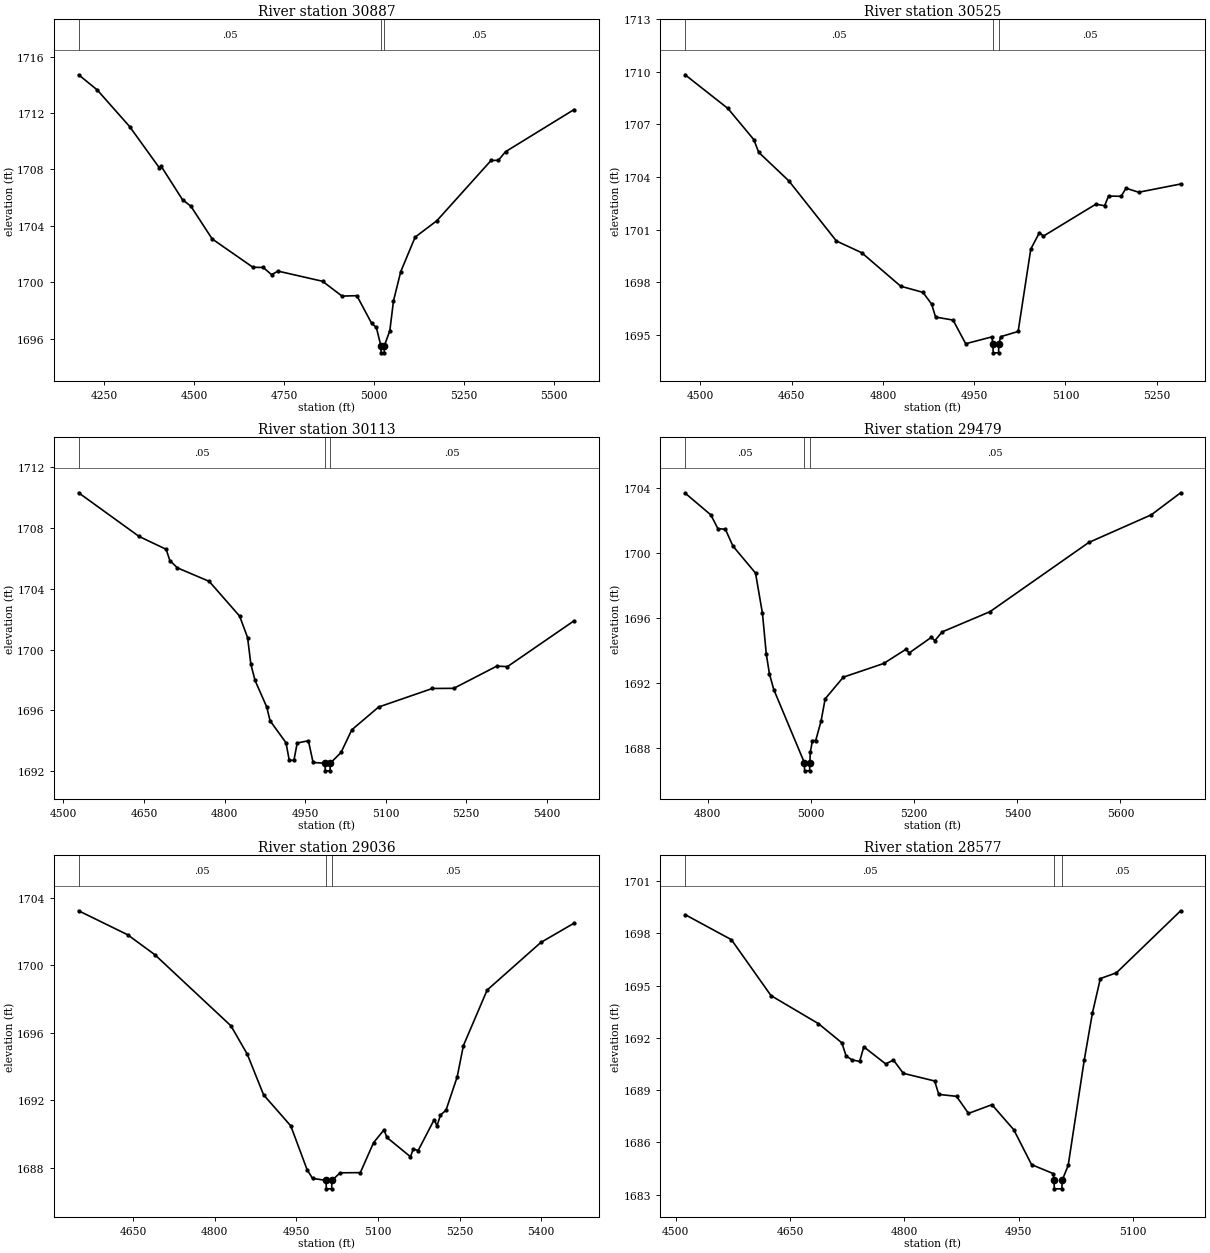
Type RM Length L Ch R = 1,30887,362,362,362
BEGIN DESCRIPTION:
Threemile Creek 57.0
END DESCRIPTION:
XS GIS Cut Line= 3
      1643104.99      6935288.04      1642905.00      6936088.00
      1642955.00      6936637.95
#Sta/Elev= 30
  4179.4 1714.71  4230.9 1713.64  4321.1 1711.04  4403.6 1708.12  4408.7 1708.23
  4468.0 1705.86  4491.2 1705.40  4550.4 1703.08  4663.8 1701.07  4692.2 1701.06
  4715.4 1700.55  4733.4 1700.80  4857.1 1700.08  4911.2 1699.03  4952.4 1699.06
  4993.7 1697.09  5006.5 1696.81  5019.2 1695.51  5019.7 1695.01  5028.4 1695.01
  5028.9 1695.51  5044.1 1696.59  5054.2 1698.69  5074.3 1700.76  5114.4 1703.21
  5174.7 1704.37  5325.3 1708.64  5345.4 1708.65  5365.5 1709.26  5556.2 1712.25
#Mann=3,-1,0
  4179.4    0.05       0  5019.2    0.03       0  5028.9    0.05       0
Bank Sta=5019.2,5028.9
Exp/Cntr=0.3,0.1

Type RM Length L Ch R = 1,30525,412,412,412
BEGIN DESCRIPTION:
Mapping XS de717e64
END DESCRIPTION:
XS GIS Cut Line= 2
      1642979.95      6935423.57      1642464.65      6936054.34
#Sta/Elev= 30
  4474.8 1709.83  4545.1 1707.91  4587.8 1706.13  4595.7 1705.41  4645.3 1703.78
  4723.5 1700.35  4765.1 1699.68  4829.2 1697.77  4865.7 1697.42  4880.0 1696.75
  4886.5 1696.01  4915.2 1695.84  4936.0 1694.49  4979.1 1694.88  4980.7 1694.47
  4981.2 1693.97  4990.0 1693.97  4990.5 1694.47  4993.5 1694.89  5022.2 1695.19
  5043.0 1699.89  5057.3 1700.83  5063.8 1700.63  5150.0 1702.45  5164.3 1702.36
  5170.8 1702.91  5191.6 1702.90  5199.5 1703.36  5220.3 1703.13  5289.3 1703.60
#Mann=3,-1,0
  4474.8    0.05       0  4980.7    0.05       0  4990.5    0.05       0
Bank Sta=4980.7,4990.5
Exp/Cntr=0.3,0.1

Type RM Length L Ch R = 1,30113,634,634,634
BEGIN DESCRIPTION:
Threemile Creek 56.0
END DESCRIPTION:
XS GIS Cut Line= 3
      1642774.20      6935250.02      1642388.50      6935520.01
      1642382.08      6935972.16
#Sta/Elev= 30
  4528.3 1710.32  4640.7 1707.45  4691.3 1706.60  4698.2 1705.86  4712.2 1705.38
  4771.5 1704.49  4828.2 1702.20  4843.0 1700.79  4849.1 1699.03  4856.9 1697.97
  4878.7 1696.22  4884.8 1695.32  4914.5 1693.87  4920.6 1692.72  4929.3 1692.71
  4935.4 1693.85  4956.3 1694.00  4965.0 1692.57  4987.2 1692.52  4987.7 1692.02
  4996.5 1692.02  4997.0 1692.52  5017.1 1693.23  5037.1 1694.72  5087.1 1696.22
  5187.1 1697.44  5227.1 1697.45  5307.1 1698.91  5327.1 1698.88  5451.3 1701.90
#Mann=3,-1,0
  4528.3    0.05       0  4987.2    0.05       0  4997.0    0.05       0
Bank Sta=4987.2,4997
Exp/Cntr=0.3,0.1

Type RM Length L Ch R = 1,29479,443,443,443
BEGIN DESCRIPTION:
Threemile Creek 55.0
END DESCRIPTION:
XS GIS Cut Line= 3
      1641705.00      6935438.00      1641855.00      6935638.00
      1642404.97      6936087.98
#Sta/Elev= 30
  4756.0 1703.67  4806.0 1702.33  4819.5 1701.49  4834.1 1701.45  4848.7 1700.42
  4892.5 1698.76  4906.0 1696.28  4913.3 1693.81  4919.5 1692.57  4927.9 1691.61
  4987.2 1687.12  4987.7 1686.62  4997.3 1686.62  4997.8 1687.12  4998.7 1687.76
  5002.9 1688.48  5009.2 1688.48  5019.6 1689.68  5027.5 1691.04  5062.7 1692.37
  5140.9 1693.21  5184.0 1694.08  5190.5 1693.86  5233.5 1694.82  5240.0 1694.61
  5254.4 1695.15  5347.0 1696.39  5538.6 1700.64  5659.9 1702.34  5716.6 1703.69
#Mann=3,-1,0
  4756.0    0.05       0  4987.2    0.03       0  4997.8    0.05       0
Bank Sta=4987.2,4997.8
Exp/Cntr=0.3,0.1

Type RM Length L Ch R = 1,29036,459,459,459
BEGIN DESCRIPTION:
Threemile Creek 54.0
END DESCRIPTION:
XS GIS Cut Line= 3
      1641555.00      6935488.03      1641555.00      6935938.00
      1641654.99      6936387.96
#Sta/Elev= 30
  4549.8 1703.24  4639.8 1701.82  4689.8 1700.64  4829.8 1696.42  4859.8 1694.74
  4889.8 1692.33  4939.8 1690.49  4969.8 1687.89  4979.8 1687.38  5004.6 1687.26
  5005.1 1686.76  5014.9 1686.76  5015.4 1687.26  5030.5 1687.71  5067.6 1687.72
  5092.0 1689.50  5111.2 1690.26  5116.3 1689.81  5159.8 1688.66  5164.9 1689.12
  5173.9 1689.03  5203.4 1690.86  5208.5 1690.49  5214.9 1691.13  5225.1 1691.42
  5245.6 1693.39  5257.1 1695.25  5300.7 1698.54  5399.3 1701.36  5460.7 1702.51
#Mann=3,-1,0
  4549.8    0.05       0  5004.6    0.03       0  5015.4    0.05       0
Bank Sta=5004.6,5015.4
Exp/Cntr=0.3,0.1

Type RM Length L Ch R = 1,28577,467,467,467
BEGIN DESCRIPTION:
Threemile Creek 53.0
END DESCRIPTION:
XS GIS Cut Line= 3
      1641354.99      6935638.03      1641155.00      6936088.00
      1641105.01      6936237.98
#Sta/Elev= 30
  4512.2 1699.07  4573.0 1697.63  4625.0 1694.42  4687.3 1692.81  4718.0 1691.71
  4723.5 1690.96  4731.0 1690.74  4741.3 1690.64  4746.8 1691.48  4775.5 1690.50
  4785.7 1690.72  4798.7 1689.96  4839.8 1689.52  4845.2 1688.75  4868.5 1688.64
  4884.2 1687.66  4915.0 1688.16  4943.7 1686.72  4967.0 1684.72  4995.7 1684.20
  4996.4 1683.83  4996.9 1683.33  5006.8 1683.33  5007.3 1683.83  5015.1 1684.68
  5036.2 1690.73  5046.8 1693.40  5057.3 1695.40  5078.4 1695.73  5162.7 1699.29
#Mann=3,-1,0
  4512.2    0.05       0  4996.4    0.05       0  5007.3    0.05       0
Bank Sta=4996.4,5007.3
Exp/Cntr=0.3,0.1

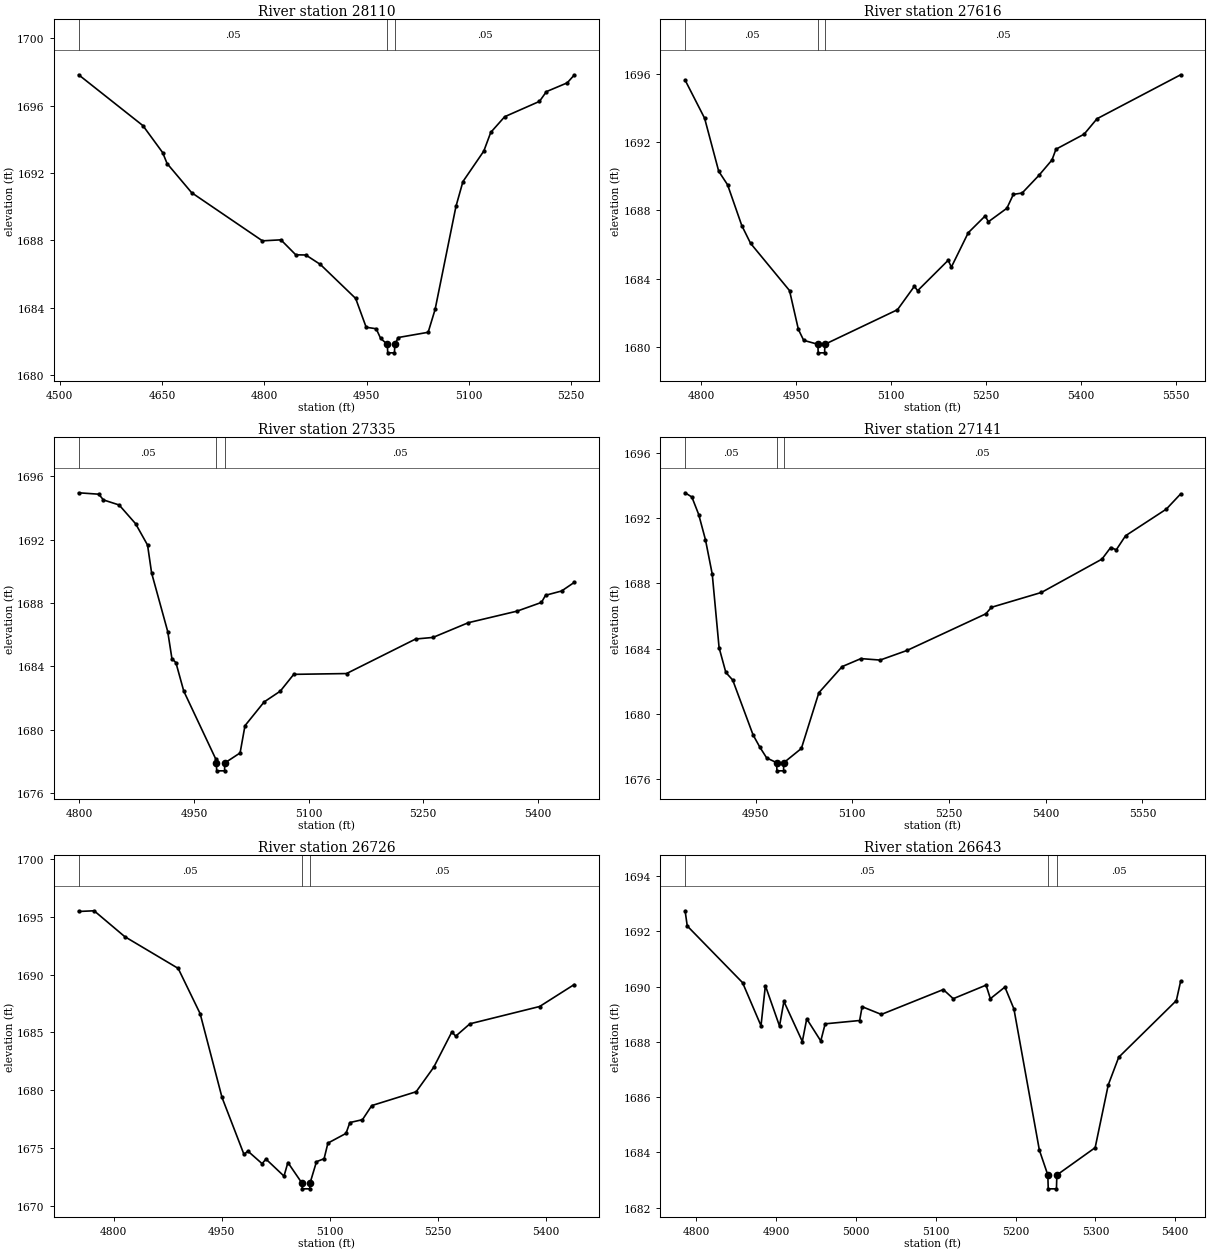
Type RM Length L Ch R = 1,28110,494,494,494
BEGIN DESCRIPTION:
Threemile Creek 52.0
END DESCRIPTION:
XS GIS Cut Line= 3
      1641204.99      6935538.00      1640805.00      6935788.00
      1640755.01      6936037.96
#Sta/Elev= 30
  4527.9 1697.83  4622.2 1694.81  4651.1 1693.21  4657.6 1692.56  4693.6 1690.83
  4797.4 1687.97  4824.5 1688.03  4846.3 1687.14  4861.0 1687.13  4882.3 1686.57
  4934.1 1684.55  4949.5 1682.84  4964.2 1682.75  4970.7 1682.18  4980.6 1681.82
  4981.1 1681.32  4991.0 1681.32  4991.5 1681.82  4996.6 1682.23  5040.4 1682.54
  5050.6 1683.90  5081.2 1690.02  5091.4 1691.49  5122.0 1693.30  5132.2 1694.41
  5152.6 1695.34  5203.6 1696.25  5213.8 1696.83  5244.3 1697.35  5254.5 1697.81
#Mann=3,-1,0
  4527.9    0.05       0  4980.6    0.05       0  4991.5    0.05       0
Bank Sta=4980.6,4991.5
Exp/Cntr=0.3,0.1

Type RM Length L Ch R = 1,27616,281,281,281
BEGIN DESCRIPTION:
Threemile Creek 51.0
END DESCRIPTION:
XS GIS Cut Line= 3
      1640555.01      6935237.99      1640455.00      6935438.00
      1640554.99      6935987.96
#Sta/Elev= 30
  4774.7 1695.62  4805.5 1693.39  4827.8 1690.29  4841.8 1689.50  4864.2 1687.12
  4878.1 1686.08  4939.6 1683.32  4953.6 1681.05  4962.0 1680.41  4984.4 1680.18
  4984.9 1679.68  4995.0 1679.68  4995.5 1680.18  5110.1 1682.20  5136.8 1683.57
  5141.9 1683.31  5190.2 1685.09  5195.2 1684.69  5221.9 1686.70  5248.6 1687.68
  5253.7 1687.34  5282.9 1688.13  5293.1 1688.94  5307.0 1689.02  5333.7 1690.06
  5354.1 1690.95  5360.4 1691.58  5404.9 1692.46  5425.2 1693.36  5557.3 1695.93
#Mann=3,-1,0
  4774.7    0.05       0  4984.4    0.05       0  4995.5    0.05       0
Bank Sta=4984.4,4995.5
Exp/Cntr=0.3,0.1

Type RM Length L Ch R = 1,27335,194,194,194
BEGIN DESCRIPTION:
Mapping XS 422c215c
END DESCRIPTION:
XS GIS Cut Line= 2
      1640162.06      6935177.17      1640363.28      6935793.66
#Sta/Elev= 30
  4799.0 1694.96  4825.4 1694.87  4831.4 1694.51  4852.0 1694.19  4873.5 1693.01
  4889.2 1691.66  4894.5 1689.90  4915.6 1686.20  4921.1 1684.49  4926.3 1684.24
  4936.6 1682.44  4978.7 1678.13  4979.2 1677.91  4979.7 1677.41  4989.9 1677.41
  4990.4 1677.91  5010.3 1678.54  5016.7 1680.26  5041.8 1681.76  5062.9 1682.44
  5080.5 1683.50  5149.6 1683.55  5240.0 1685.73  5262.7 1685.83  5309.0 1686.76
  5372.8 1687.49  5404.7 1688.04  5410.0 1688.49  5431.0 1688.76  5447.5 1689.30
#Mann=3,-1,0
  4799.0    0.05       0  4979.2    0.05       0  4990.4    0.05       0
Bank Sta=4979.2,4990.4
Exp/Cntr=0.3,0.1

Type RM Length L Ch R = 1,27141,415,415,415
BEGIN DESCRIPTION:
Threemile Creek 50.0
END DESCRIPTION:
XS GIS Cut Line= 3
      1639905.02      6935388.01      1640055.00      6935438.00
      1640404.99      6935937.99
#Sta/Elev= 30
  4840.8 1693.55  4851.3 1693.29  4861.9 1692.22  4872.4 1690.67  4882.9 1688.57
  4893.5 1684.07  4904.0 1682.55  4914.6 1682.09  4946.2 1678.73  4956.7 1677.98
  4967.3 1677.32  4982.7 1677.03  4983.2 1676.53  4993.4 1676.53  4993.9 1677.03
  5021.1 1677.90  5048.2 1681.31  5084.3 1682.91  5113.5 1683.40  5143.2 1683.31
  5185.0 1683.90  5307.1 1686.14  5315.8 1686.54  5393.4 1687.45  5487.2 1689.49
  5500.7 1690.20  5509.4 1690.06  5523.8 1690.92  5587.0 1692.55  5609.2 1693.48
#Mann=3,-1,0
  4840.8    0.05       0  4982.7    0.03       0  4993.9    0.05       0
Bank Sta=4982.7,4993.9
Exp/Cntr=0.3,0.1

Type RM Length L Ch R = 1,26726,83,83,83
BEGIN DESCRIPTION:
Mapping XS 918ed45e
END DESCRIPTION:
XS GIS Cut Line= 2
      1639574.87      6935663.57      1640221.00      6935901.06
#Sta/Elev= 30
  4751.1 1695.48  4772.6 1695.54  4815.2 1693.30  4889.4 1690.55  4919.9 1686.63
  4950.3 1679.37  4980.8 1674.44  4986.2 1674.73  5006.0 1673.64  5011.3 1674.04
  5036.4 1672.56  5041.8 1673.74  5061.3 1671.96  5061.8 1671.46  5072.1 1671.46
  5072.6 1671.96  5081.5 1673.81  5092.1 1674.07  5097.4 1675.42  5122.5 1676.26
  5127.9 1677.20  5145.4 1677.45  5158.3 1678.67  5220.0 1679.87  5244.4 1681.99
  5269.6 1685.05  5274.9 1684.68  5294.6 1685.75  5391.5 1687.25  5439.5 1689.15
#Mann=3,-1,0
  4751.1    0.05       0  5061.3    0.03       0  5072.6    0.05       0
Bank Sta=5061.3,5072.6
Exp/Cntr=0.3,0.1

Type RM Length L Ch R = 1,26643,87,87,87
BEGIN DESCRIPTION:
Threemile Creek 49.0
END DESCRIPTION:
XS GIS Cut Line= 3
      1639577.03      6935732.15      1639776.34      6935822.16
      1640149.04      6935973.37
#Sta/Elev= 30
  4785.9 1692.74  4788.6 1692.19  4857.9 1690.14  4881.0 1688.58  4886.5 1690.03
  4904.2 1688.57  4909.7 1689.46  4932.8 1688.01  4938.3 1688.83  4955.9 1688.03
  4961.4 1688.65  5004.6 1688.77  5007.7 1689.27  5031.8 1688.99  5109.4 1689.89
  5121.9 1689.56  5163.0 1690.05  5168.4 1689.56  5186.6 1689.98  5197.9 1689.19
  5229.8 1684.08  5240.4 1683.18  5240.9 1682.68  5251.2 1682.68  5251.7 1683.18
  5299.7 1684.17  5316.1 1686.44  5329.2 1687.44  5401.4 1689.49  5406.8 1690.19
#Mann=3,-1,0
  4785.9    0.05       0  5240.4    0.05       0  5251.7    0.05       0
Bank Sta=5240.4,5251.7
Exp/Cntr=0.3,0.1

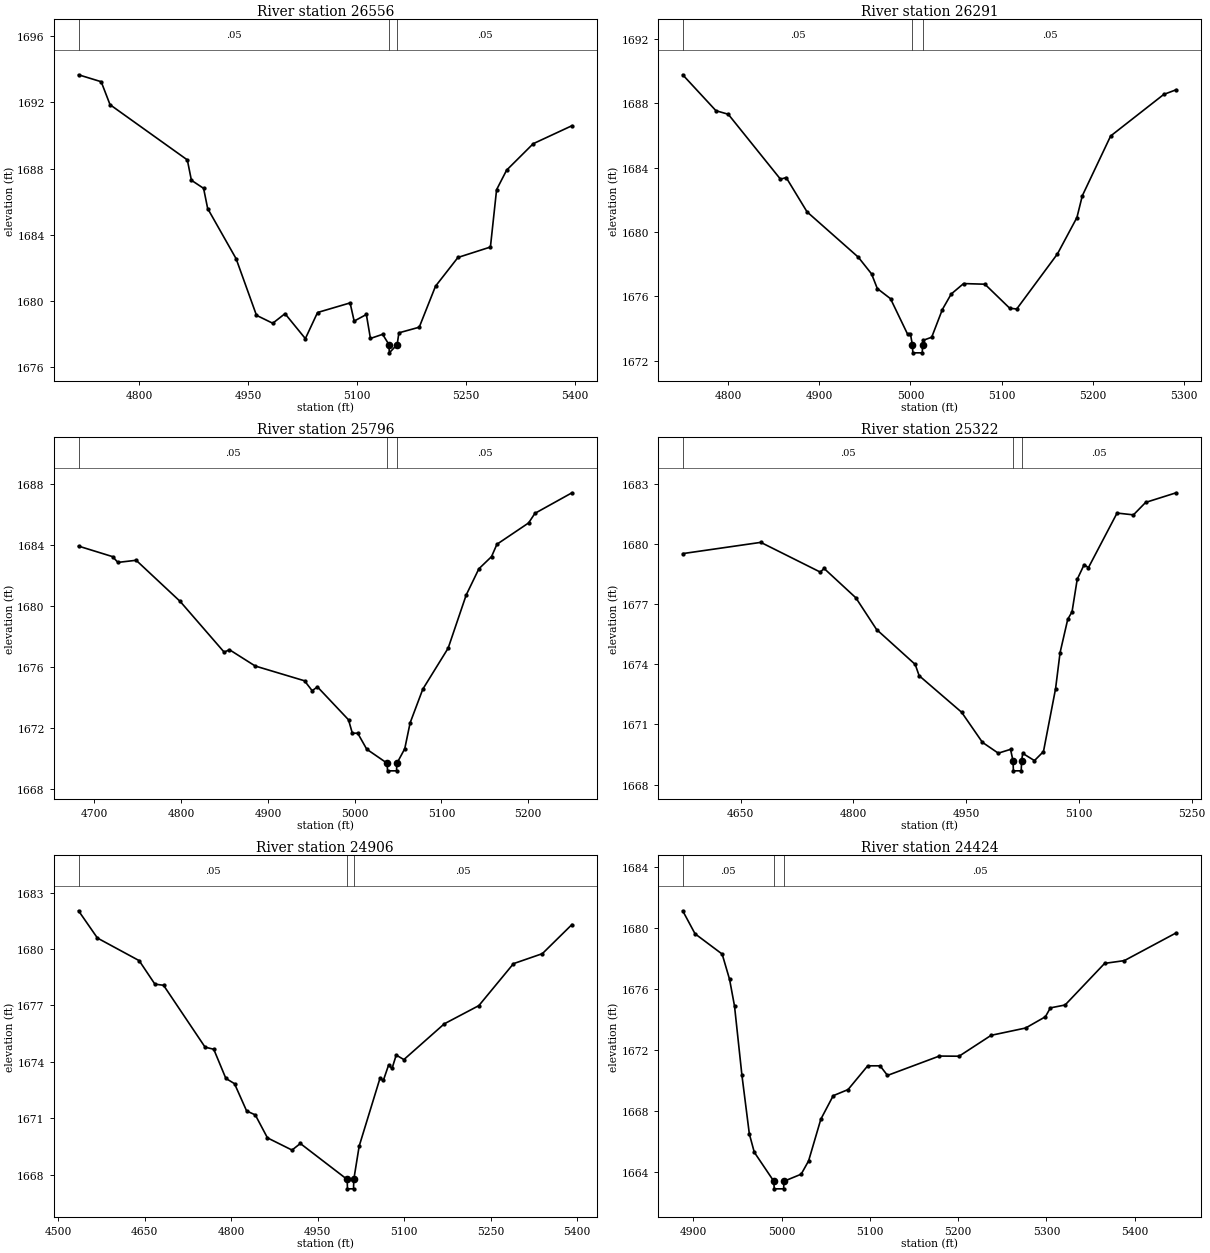
Type RM Length L Ch R = 1,26556,265,265,265
BEGIN DESCRIPTION:
Mapping XS 26b4cc53
END DESCRIPTION:
XS GIS Cut Line= 2
      1639457.08      6935755.74      1640065.61      6936057.87
#Sta/Elev= 30
  4716.5 1693.67  4747.7 1693.25  4759.9 1691.86  4866.3 1688.52  4871.9 1687.29
  4888.7 1686.80  4894.3 1685.58  4933.5 1682.54  4961.5 1679.12  4983.9 1678.64
  5000.8 1679.22  5028.8 1677.71  5045.6 1679.29  5090.4 1679.87  5096.0 1678.77
  5112.8 1679.17  5118.4 1677.72  5135.2 1677.97  5143.9 1677.35  5144.4 1676.85
  5155.2 1677.35  5157.6 1678.06  5185.6 1678.40  5208.0 1680.88  5238.9 1682.62
  5283.6 1683.25  5292.1 1686.72  5305.9 1687.90  5342.5 1689.50  5395.9 1690.59
#Mann=3,-1,0
  4716.5    0.05       0  5143.9    0.05       0  5155.2    0.05       0
Bank Sta=5143.9,5155.2
Exp/Cntr=0.3,0.1

Type RM Length L Ch R = 1,26291,495,495,495
BEGIN DESCRIPTION:
Threemile Creek 48.0
END DESCRIPTION:
XS GIS Cut Line= 3
      1639404.99      6935887.98      1639555.00      6936088.00
      1639805.03      6936238.02
#Sta/Elev= 30
  4750.0 1689.76  4786.5 1687.53  4800.0 1687.31  4857.3 1683.28  4863.6 1683.38
  4886.5 1681.25  4942.7 1678.44  4957.3 1677.40  4963.6 1676.49  4978.1 1675.86
  4996.9 1673.65  5000.0 1673.65  5002.1 1673.00  5002.6 1672.50  5012.9 1672.50
  5013.4 1673.00  5013.6 1673.27  5023.3 1673.47  5035.0 1675.19  5044.7 1676.15
  5058.3 1676.80  5081.7 1676.76  5108.9 1675.27  5116.6 1675.22  5161.3 1678.64
  5182.7 1680.90  5188.6 1682.25  5219.7 1685.96  5278.0 1688.54  5291.6 1688.83
#Mann=3,-1,0
  4750.0    0.05       0  5002.1    0.03       0  5013.4    0.05       0
Bank Sta=5002.1,5013.4
Exp/Cntr=0.3,0.1

Type RM Length L Ch R = 1,25796,474,474,474
BEGIN DESCRIPTION:
Threemile Creek 47.0
END DESCRIPTION:
XS GIS Cut Line= 3
      1639024.18      6936175.71      1639205.00      6936438.00
      1639405.02      6936588.01
#Sta/Elev= 30
  4681.8 1683.93  4721.0 1683.24  4727.2 1682.86  4748.2 1683.00  4798.9 1680.30
  4849.6 1676.97  4855.7 1677.13  4885.4 1676.06  4942.2 1675.09  4951.0 1674.44
  4957.1 1674.69  4992.9 1672.53  4997.3 1671.65  5003.5 1671.65  5013.9 1670.60
  5037.4 1669.68  5037.9 1669.18  5048.2 1669.18  5048.7 1669.68  5057.7 1670.63
  5063.9 1672.33  5078.5 1674.54  5107.7 1677.23  5128.5 1680.72  5143.1 1682.44
  5157.7 1683.24  5163.9 1684.05  5200.4 1685.45  5207.7 1686.08  5250.4 1687.43
#Mann=3,-1,0
  4681.8    0.05       0  5037.4    0.03       0  5048.7    0.05       0
Bank Sta=5037.4,5048.7
Exp/Cntr=0.3,0.1

Type RM Length L Ch R = 1,25322,416,416,416
BEGIN DESCRIPTION:
Threemile Creek 46.0
END DESCRIPTION:
XS GIS Cut Line= 3
      1638707.04      6936227.15      1638805.00      6936638.00
      1638916.70      6936843.66
#Sta/Elev= 30
  4572.9 1679.51  4676.8 1680.07  4755.9 1678.59  4761.0 1678.77  4803.2 1677.31
  4830.8 1675.73  4882.2 1673.99  4887.4 1673.43  4943.9 1671.61  4971.6 1670.11
  4992.7 1669.57  5009.0 1669.76  5012.3 1669.19  5012.8 1668.69  5023.2 1668.69
  5023.7 1669.19  5025.2 1669.56  5040.8 1669.20  5052.8 1669.65  5068.9 1672.78
  5074.9 1674.58  5085.1 1676.24  5090.8 1676.61  5097.7 1678.23  5106.9 1678.96
  5112.6 1678.81  5150.7 1681.53  5172.5 1681.44  5188.7 1682.06  5229.3 1682.54
#Mann=3,-1,0
  4572.9    0.05       0  5012.3    0.03       0  5023.7    0.05       0
Bank Sta=5012.3,5023.7
Exp/Cntr=0.3,0.1

Type RM Length L Ch R = 1,24906,482,482,482
BEGIN DESCRIPTION:
Threemile Creek 45.0
END DESCRIPTION:
XS GIS Cut Line= 3
      1638177.75      6936400.73      1638488.47      6936863.60
      1638786.36      6936867.88
#Sta/Elev= 30
  4535.6 1682.03  4568.4 1680.58  4640.7 1679.38  4668.0 1678.13  4683.0 1678.07
  4755.0 1674.78  4770.0 1674.67  4791.0 1673.12  4806.0 1672.84  4827.0 1671.39
  4842.0 1671.18  4863.1 1669.96  4905.7 1669.31  4920.1 1669.66  5001.3 1667.75
  5001.8 1667.25  5012.3 1667.25  5012.8 1667.75  5022.1 1669.52  5058.1 1673.12
  5064.1 1673.02  5073.1 1673.83  5079.1 1673.65  5086.3 1674.36  5099.6 1674.12
  5169.6 1676.02  5229.6 1676.99  5289.6 1679.22  5339.6 1679.75  5391.0 1681.30
#Mann=3,-1,0
  4535.6    0.05       0  5001.3    0.05       0  5012.8    0.05       0
Bank Sta=5001.3,5012.8
Exp/Cntr=0.3,0.1

Type RM Length L Ch R = 1,24424,443,443,443
BEGIN DESCRIPTION:
Threemile Creek 44.0
END DESCRIPTION:
XS GIS Cut Line= 3
      1638205.00      6937138.00      1638305.00      6937088.00
      1638704.98      6936888.01
#Sta/Elev= 30
  4887.9 1681.13  4901.9 1679.62  4932.6 1678.29  4941.0 1676.63  4946.6 1674.88
  4955.0 1670.34  4963.4 1666.49  4969.0 1665.29  4991.1 1663.39  4991.6 1662.89
  5002.2 1662.89  5002.7 1663.39  5022.1 1663.85  5030.5 1664.72  5044.4 1667.46
  5058.4 1669.00  5075.2 1669.40  5097.5 1670.96  5111.5 1670.96  5119.9 1670.33
  5178.6 1671.60  5201.0 1671.59  5237.3 1672.96  5276.4 1673.44  5298.8 1674.18
  5304.4 1674.76  5321.1 1674.95  5365.9 1677.68  5388.2 1677.86  5446.9 1679.68
#Mann=3,-1,0
  4887.9    0.05       0  4991.1    0.03       0  5002.7    0.05       0
Bank Sta=4991.1,5002.7
Exp/Cntr=0.3,0.1

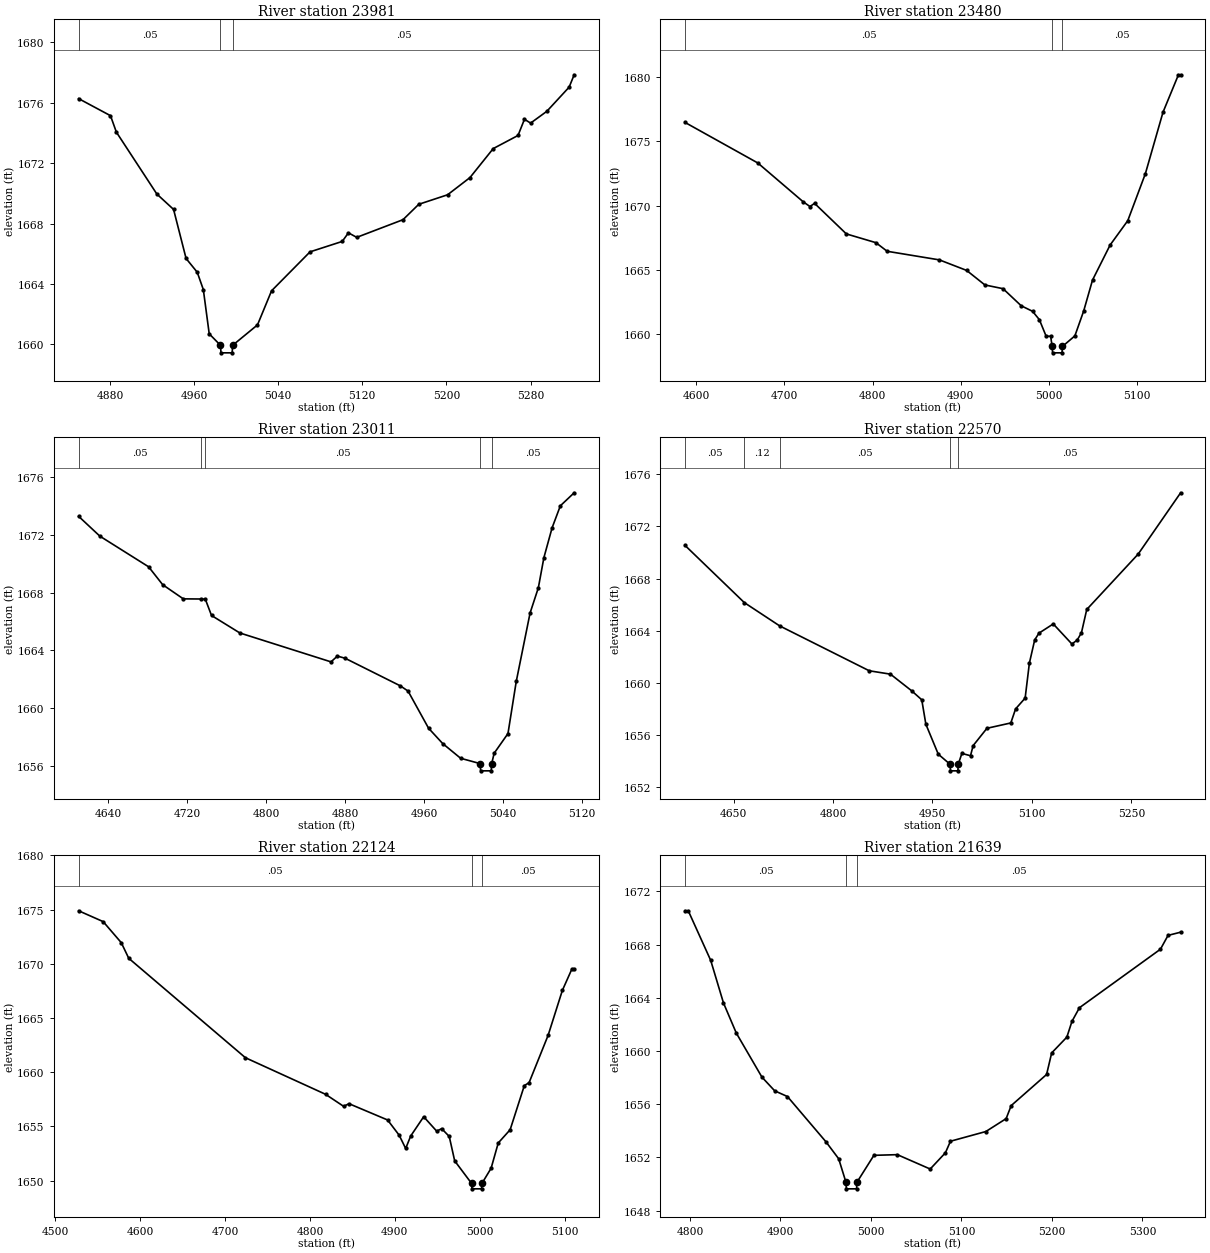
Type RM Length L Ch R = 1,23981,501,501,501
BEGIN DESCRIPTION:
Threemile Creek 43.0
END DESCRIPTION:
XS GIS Cut Line= 3
      1638505.00      6937438.00      1638637.76      6937368.60
      1638910.31      6937198.08
#Sta/Elev= 30
  4850.2 1676.28  4880.5 1675.15  4886.1 1674.06  4924.6 1669.96  4940.5 1668.94
  4952.4 1665.69  4963.0 1664.78  4968.8 1663.63  4974.4 1660.70  4985.1 1659.94
  4985.6 1659.44  4996.2 1659.44  4996.7 1659.94  5020.3 1661.29  5033.7 1663.55
  5070.3 1666.13  5100.9 1666.82  5106.8 1667.39  5114.7 1667.09  5158.7 1668.26
  5173.7 1669.28  5201.1 1669.91  5222.4 1671.05  5244.5 1672.97  5268.1 1673.84
  5274.2 1674.91  5280.1 1674.66  5295.5 1675.44  5316.7 1677.04  5321.5 1677.86
#Mann=3,-1,0
  4850.2    0.05       0  4985.1    0.03       0  4996.7    0.05       0
Bank Sta=4985.1,4996.7
Exp/Cntr=0.3,0.1

Type RM Length L Ch R = 1,23480,469,469,469
BEGIN DESCRIPTION:
Threemile Creek 42.0
END DESCRIPTION:
XS GIS Cut Line= 3
      1638505.00      6937638.00      1638905.00      6937738.00
      1639054.99      6937738.00
#Sta/Elev= 30
  4587.3 1676.46  4669.8 1673.31  4721.3 1670.29  4729.0 1669.92  4734.2 1670.17
  4770.3 1667.79  4803.8 1667.11  4816.6 1666.44  4875.9 1665.77  4906.8 1664.95
  4927.5 1663.82  4948.1 1663.53  4968.7 1662.20  4981.6 1661.77  4989.3 1661.12
  4997.0 1659.83  5002.1 1659.83  5003.8 1659.04  5004.3 1658.54  5015.0 1658.54
  5015.5 1659.04  5029.6 1659.86  5039.6 1661.80  5049.6 1664.20  5069.6 1666.93
  5089.6 1668.82  5109.6 1672.48  5129.6 1677.26  5147.1 1680.17  5149.6 1680.17
#Mann=3,-1,0
  4587.3    0.05       0  5003.8    0.05       0  5015.5    0.05       0
Bank Sta=5003.8,5015.5
Exp/Cntr=0.3,0.1

Type RM Length L Ch R = 1,23011,441,441,441
BEGIN DESCRIPTION:
Threemile Creek 41.0
END DESCRIPTION:
XS GIS Cut Line= 3
      1638455.01      6937838.01      1638705.00      6938138.00
      1638805.00      6938188.00
#Sta/Elev= 30
  4610.0 1673.28  4631.5 1671.91  4680.9 1669.79  4695.2 1668.55  4716.1 1667.57
  4734.0 1667.56  4738.4 1667.55  4744.7 1666.42  4773.4 1665.21  4865.8 1663.21
  4872.3 1663.61  4880.1 1663.46  4936.1 1661.55  4943.9 1661.19  4964.7 1658.62
  4979.0 1657.56  4997.2 1656.54  5017.0 1656.17  5017.5 1655.67  5028.2 1655.67
  5028.7 1656.17  5031.2 1656.89  5045.2 1658.25  5053.6 1661.86  5067.6 1666.59
  5076.0 1668.34  5081.6 1670.42  5089.9 1672.48  5098.3 1674.01  5112.3 1674.91
#Mann=5,-1,0
  4610.0    0.05       0  4734.0    0.12       0  4738.4    0.05       0
  5017.0    0.05       0  5028.7    0.05       0
Bank Sta=5017,5028.7
Exp/Cntr=0.3,0.1

Type RM Length L Ch R = 1,22570,446,446,446
BEGIN DESCRIPTION:
Threemile Creek 40.0
END DESCRIPTION:
XS GIS Cut Line= 3
      1638205.01      6937988.01      1638355.00      6938388.00
      1638554.97      6938637.97
#Sta/Elev= 30
  4577.0 1670.54  4666.3 1666.15  4719.6 1664.36  4854.7 1660.91  4886.7 1660.65
  4918.7 1659.37  4933.9 1658.68  4940.1 1656.80  4958.8 1654.50  4976.7 1653.72
  4977.2 1653.22  4988.4 1653.22  4988.9 1653.72  4994.4 1654.56  5007.4 1654.38
  5011.4 1655.16  5032.2 1656.49  5068.2 1656.90  5075.4 1657.98  5089.8 1658.81
  5096.2 1661.50  5104.2 1663.28  5110.6 1663.80  5132.2 1664.51  5160.3 1662.97
  5168.3 1663.27  5174.7 1663.83  5182.7 1665.62  5260.3 1669.88  5324.3 1674.59
#Mann=5,-1,0
  4577.0    0.05       0  4666.3    0.12       0  4719.6    0.05       0
  4976.7    0.03       0  4988.9    0.05       0
Bank Sta=4976.7,4988.9
Exp/Cntr=0.3,0.1

Type RM Length L Ch R = 1,22124,485,485,485
BEGIN DESCRIPTION:
Threemile Creek 39.0
END DESCRIPTION:
XS GIS Cut Line= 3
      1637704.98      6938087.96      1637955.00      6938488.00
      1638004.98      6938587.96
#Sta/Elev= 30
  4527.7 1674.89  4556.6 1673.89  4577.9 1671.95  4586.7 1670.51  4724.1 1661.34
  4818.4 1657.97  4839.7 1656.86  4846.1 1657.10  4891.5 1655.60  4905.1 1654.20
  4912.8 1652.97  4918.7 1654.12  4934.0 1655.90  4949.3 1654.57  4955.2 1654.80
  4964.1 1654.08  4970.5 1651.83  4990.4 1649.75  4990.9 1649.25  5002.1 1649.25
  5002.6 1649.75  5013.4 1651.15  5021.8 1653.48  5035.8 1654.70  5052.5 1658.77
  5058.1 1659.04  5080.5 1663.40  5097.3 1667.55  5108.4 1669.50  5111.2 1669.50
#Mann=3,-1,0
  4527.7    0.05       0  4990.4    0.05       0  5002.6    0.05       0
Bank Sta=4990.4,5002.6
Exp/Cntr=0.3,0.1

Type RM Length L Ch R = 1,21639,270,270,270
BEGIN DESCRIPTION:
Threemile Creek 38.0
END DESCRIPTION:
XS GIS Cut Line= 3
      1637355.00      6938438.00      1637505.00      6938588.00
      1637804.96      6938737.98
#Sta/Elev= 30
  4794.7 1670.55  4798.2 1670.55  4823.0 1666.82  4837.1 1663.62  4851.3 1661.35
  4879.6 1658.04  4893.7 1657.01  4907.8 1656.58  4950.3 1653.18  4964.4 1651.90
  4972.4 1650.14  4972.9 1649.64  4984.1 1649.64  4984.6 1650.14  5003.3 1652.16
  5029.2 1652.21  5065.5 1651.13  5082.3 1652.35  5087.9 1653.22  5127.0 1653.95
  5149.4 1654.92  5155.0 1655.90  5194.1 1658.24  5199.7 1659.86  5216.5 1661.05
  5222.1 1662.23  5230.4 1663.26  5319.9 1667.66  5328.3 1668.70  5342.2 1668.94
#Mann=3,-1,0
  4794.7    0.05       0  4972.4    0.03       0  4984.6    0.05       0
Bank Sta=4972.4,4984.6
Exp/Cntr=0.3,0.1

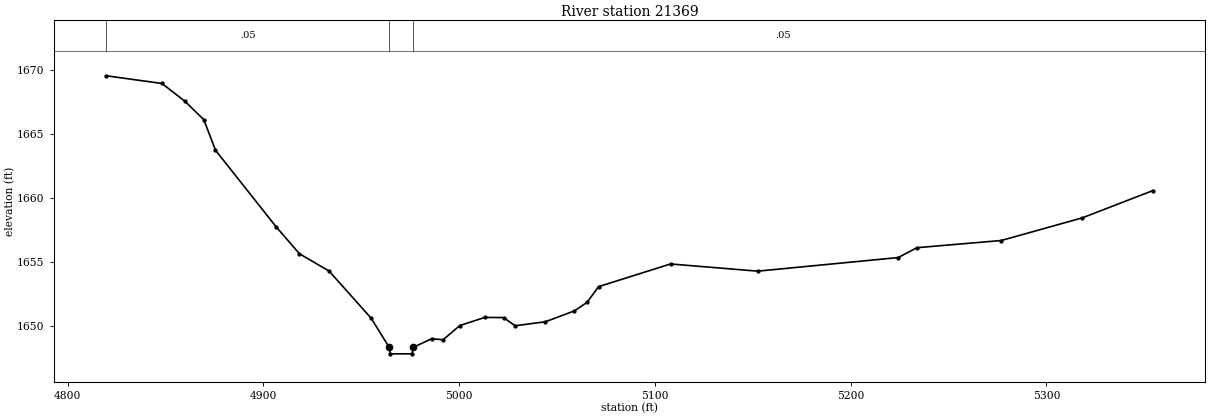
Type RM Length L Ch R = 1,21369,283,283,283
BEGIN DESCRIPTION:
Mapping XS dda8f528
END DESCRIPTION:
XS GIS Cut Line= 3
      1637140.63      6938655.05      1637517.75      6938884.32
      1637610.99      6938877.97
#Sta/Elev= 30
  4819.7 1669.54  4848.2 1668.94  4860.0 1667.54  4869.6 1666.11  4875.5 1663.74
  4906.4 1657.78  4918.4 1655.66  4933.6 1654.30  4955.0 1650.64  4964.3 1648.35
  4964.8 1647.85  4976.0 1647.85  4976.5 1648.35  4985.9 1649.03  4991.8 1648.95
  5000.4 1650.06  5013.1 1650.69  5022.7 1650.68  5028.6 1650.04  5044.0 1650.35
  5058.9 1651.20  5065.4 1651.87  5071.2 1653.09  5108.0 1654.86  5152.5 1654.30
  5224.3 1655.36  5233.9 1656.13  5276.9 1656.69  5318.4 1658.46  5354.5 1660.59
#Mann=3,-1,0
  4819.7    0.05       0  4964.3    0.03       0  4976.5    0.05       0
Bank Sta=4964.3,4976.5
Exp/Cntr=0.3,0.1