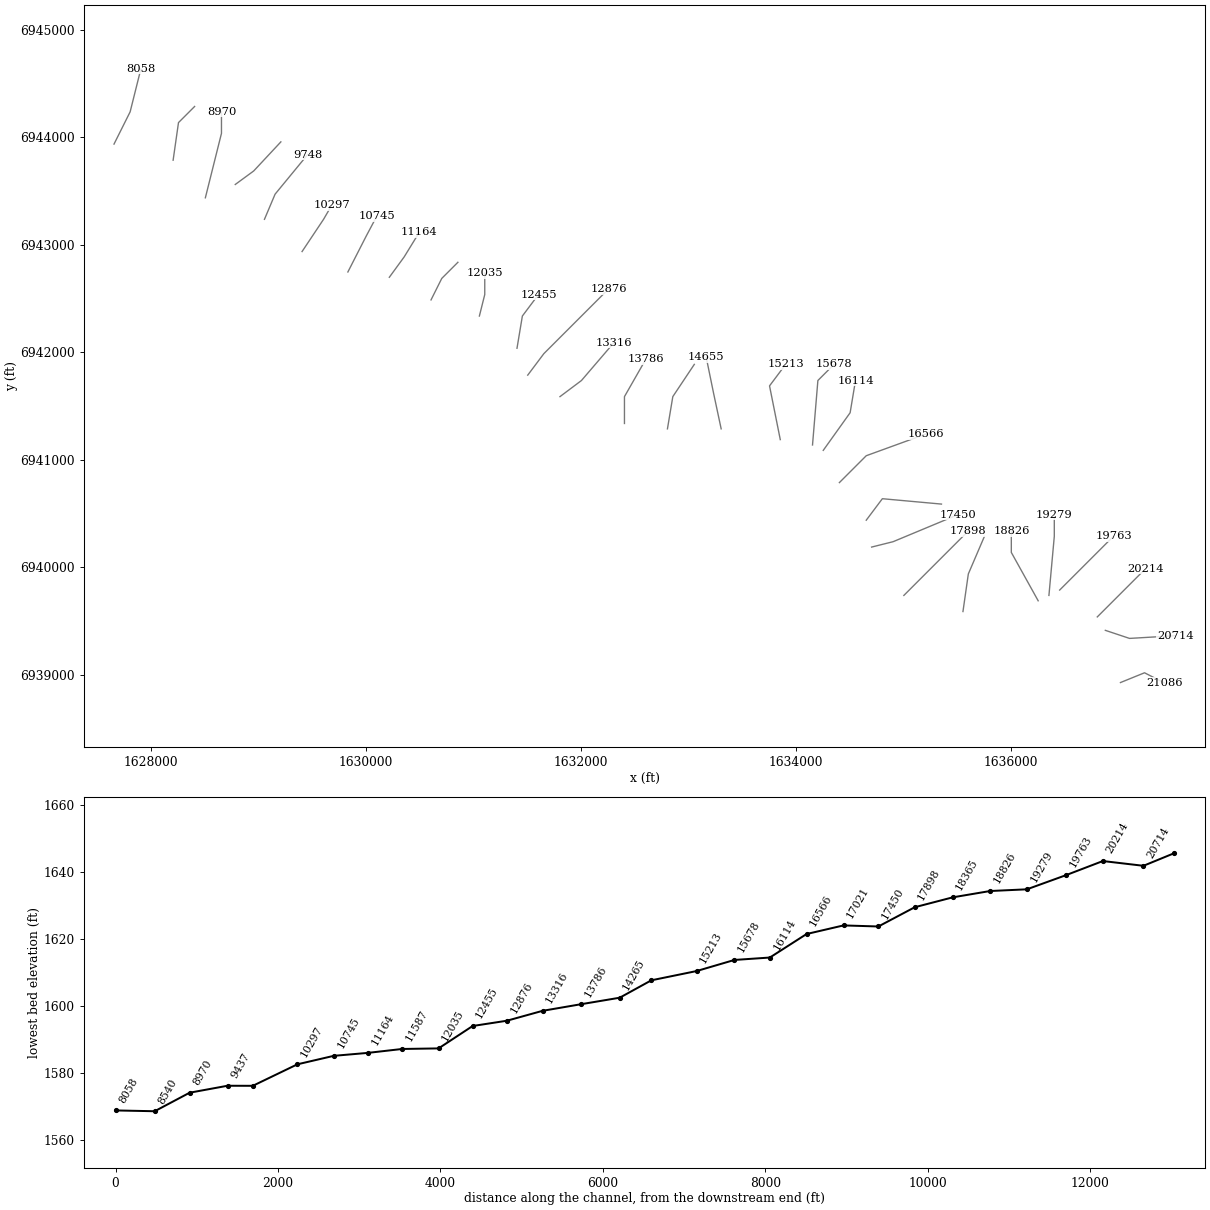
HEC-RAS study Threemile Creek.prj: Threemile Creek Base Level Engineering

--- Threemile Creek.g01 (geometry) --- (continued)

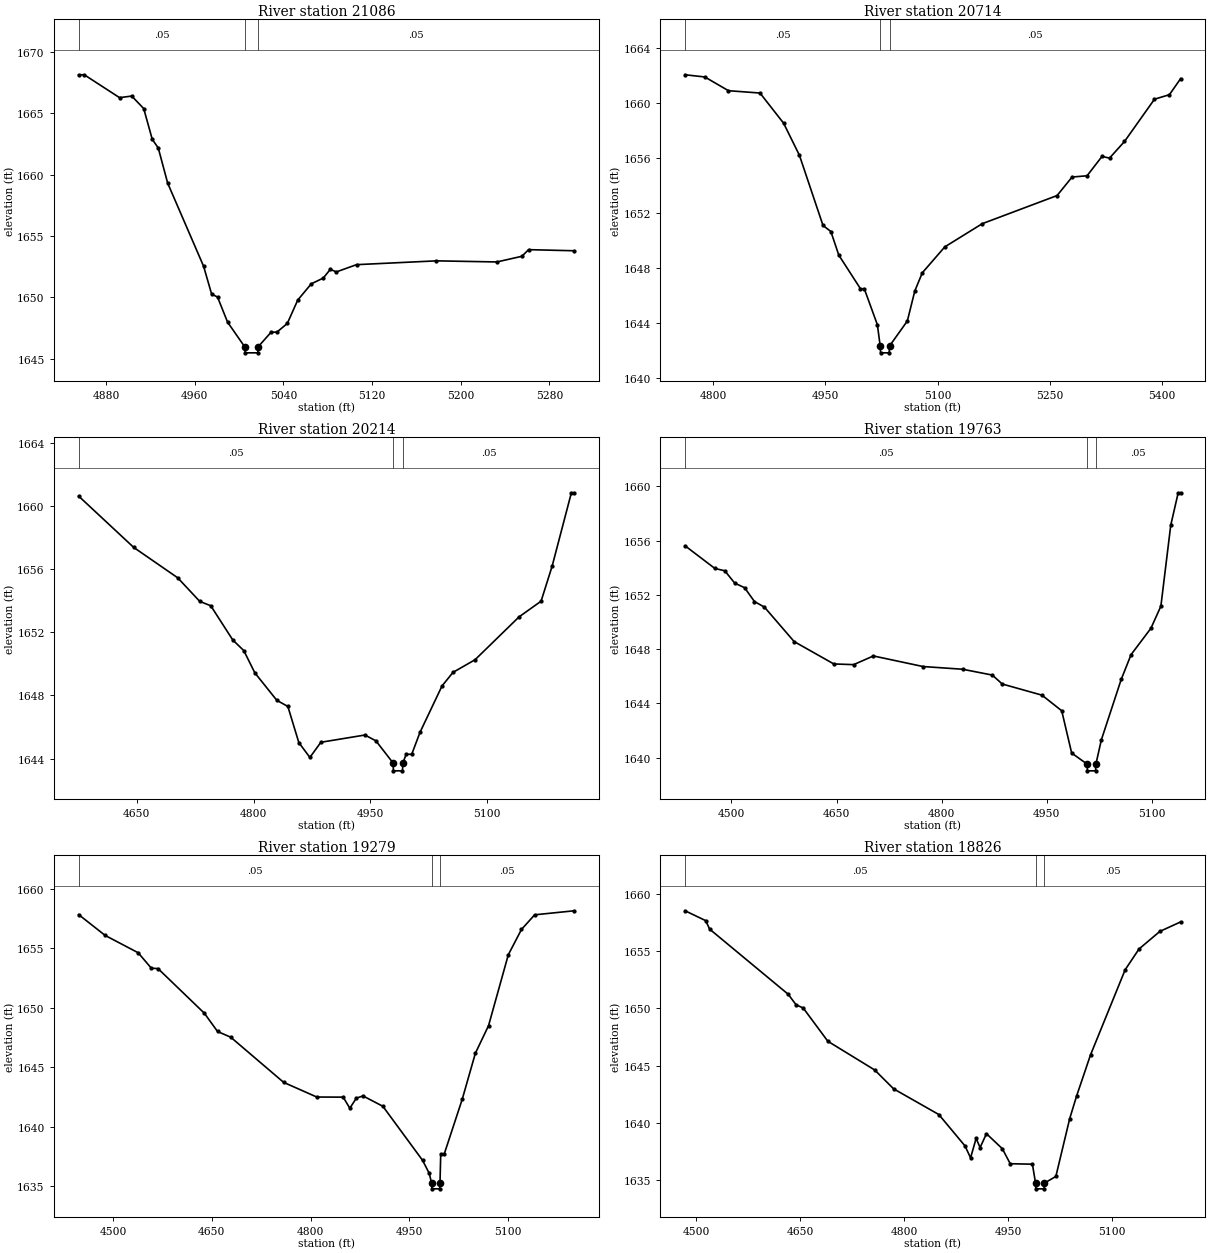
Type RM Length L Ch R = 1,21086,372,372,372
BEGIN DESCRIPTION:
Threemile Creek 37.0
END DESCRIPTION:
XS GIS Cut Line= 3
      1637020.59      6938927.18      1637244.70      6939018.22
      1637427.01      6938924.46
#Sta/Elev= 30
  4855.4 1668.11  4860.5 1668.11  4892.3 1666.25  4903.3 1666.38  4914.1 1665.36
  4921.8 1662.86  4927.2 1662.16  4935.7 1659.30  4968.1 1652.54  4975.3 1650.29
  4980.7 1650.03  4989.7 1648.00  5005.1 1646.00  5005.6 1645.50  5016.9 1645.50
  5017.4 1646.00  5028.9 1647.17  5034.3 1647.19  5043.6 1647.89  5053.0 1649.79
  5065.2 1651.11  5076.0 1651.58  5082.4 1652.29  5087.8 1652.08  5106.0 1652.67
  5178.1 1652.98  5232.6 1652.89  5255.1 1653.35  5261.2 1653.89  5302.3 1653.80
#Mann=3,-1,0
  4855.4    0.05       0  5005.1    0.05       0  5017.4    0.05       0
Bank Sta=5005.1,5017.4
Exp/Cntr=0.3,0.1

Type RM Length L Ch R = 1,20714,500,500,500
BEGIN DESCRIPTION:
Threemile Creek 36.0
END DESCRIPTION:
XS GIS Cut Line= 3
      1636879.98      6939413.01      1637105.00      6939338.00
      1637529.98      6939363.00
#Sta/Elev= 30
  4762.3 1662.06  4788.7 1661.90  4820.3 1660.90  4862.5 1660.73  4894.1 1658.53
  4915.2 1656.20  4946.8 1651.08  4957.3 1650.64  4967.9 1648.92  4996.9 1646.47
  5002.0 1646.47  5019.5 1643.85  5023.3 1642.30  5023.8 1641.80  5035.3 1641.80
  5035.8 1642.30  5059.6 1644.12  5069.6 1646.31  5079.6 1647.63  5109.7 1649.52
  5159.8 1651.21  5259.9 1653.26  5280.0 1654.61  5300.0 1654.70  5320.0 1656.11
  5330.1 1655.99  5350.1 1657.20  5390.2 1660.28  5410.2 1660.61  5425.2 1661.78
#Mann=3,-1,0
  4762.3    0.05       0  5023.3    0.05       0  5035.8    0.05       0
Bank Sta=5023.3,5035.8
Exp/Cntr=0.3,0.1

Type RM Length L Ch R = 1,20214,451,451,451
BEGIN DESCRIPTION:
Threemile Creek 35.0
END DESCRIPTION:
XS GIS Cut Line= 3
      1636805.02      6939538.02      1637105.00      6939838.00
      1637255.02      6939988.02
#Sta/Elev= 30
  4575.3 1660.63  4646.0 1657.38  4702.6 1655.45  4730.8 1653.96  4745.0 1653.68
  4773.3 1651.51  4787.4 1650.84  4801.6 1649.43  4829.8 1647.69  4844.0 1647.30
  4858.1 1645.01  4872.3 1644.07  4886.4 1645.03  4943.0 1645.49  4957.1 1645.12
  4979.1 1643.72  4979.6 1643.22  4991.2 1643.22  4991.7 1643.72  4996.0 1644.27
  5003.1 1644.27  5013.7 1645.66  5042.0 1648.60  5056.1 1649.46  5084.4 1650.26
  5141.0 1652.98  5169.2 1653.97  5183.4 1656.19  5208.1 1660.84  5211.7 1660.84
#Mann=3,-1,0
  4575.3    0.05       0  4979.1    0.03       0  4991.7    0.05       0
Bank Sta=4979.1,4991.7
Exp/Cntr=0.3,0.1

Type RM Length L Ch R = 1,19763,484,484,484
BEGIN DESCRIPTION:
Threemile Creek 34.0
END DESCRIPTION:
XS GIS Cut Line= 3
      1636454.97      6939787.97      1636855.00      6940188.00
      1636954.97      6940287.97
#Sta/Elev= 30
  4433.8 1655.62  4476.3 1653.95  4490.4 1653.78  4504.6 1652.87  4518.7 1652.53
  4532.8 1651.51  4547.0 1651.10  4589.4 1648.56  4646.0 1646.91  4674.3 1646.86
  4702.5 1647.50  4773.3 1646.72  4829.8 1646.52  4872.2 1646.09  4886.4 1645.43
  4943.0 1644.61  4971.2 1643.46  4985.4 1640.34  5007.4 1639.53  5007.9 1639.03
  5019.5 1639.03  5020.0 1639.53  5027.8 1641.32  5056.1 1645.77  5070.2 1647.60
  5098.5 1649.54  5112.7 1651.17  5126.8 1657.14  5137.4 1659.53  5140.9 1659.53
#Mann=3,-1,0
  4433.8    0.05       0  5007.4    0.05       0  5020.0    0.05       0
Bank Sta=5007.4,5020
Exp/Cntr=0.3,0.1

Type RM Length L Ch R = 1,19279,453,453,453
BEGIN DESCRIPTION:
Threemile Creek 33.0
END DESCRIPTION:
XS GIS Cut Line= 3
      1636355.00      6939738.01      1636405.00      6940288.00
      1636405.00      6940488.04
#Sta/Elev= 30
  4447.8 1657.84  4488.0 1656.09  4538.2 1654.63  4558.2 1653.33  4568.3 1653.30
  4638.6 1649.55  4658.7 1648.01  4678.7 1647.53  4759.1 1643.73  4809.3 1642.50
  4849.4 1642.49  4859.5 1641.56  4869.5 1642.41  4879.6 1642.59  4909.7 1641.72
  4969.9 1637.18  4980.0 1636.09  4983.6 1635.28  4984.1 1634.78  4995.9 1634.78
  4996.4 1635.28  4997.5 1637.67  5002.6 1637.67  5030.1 1642.30  5050.1 1646.18
  5070.1 1648.50  5100.1 1654.46  5120.1 1656.59  5140.1 1657.82  5200.1 1658.16
#Mann=3,-1,0
  4447.8    0.05       0  4983.6    0.05       0  4996.4    0.05       0
Bank Sta=4983.6,4996.4
Exp/Cntr=0.3,0.1

Type RM Length L Ch R = 1,18826,461,461,461
BEGIN DESCRIPTION:
Threemile Creek 32.0
END DESCRIPTION:
XS GIS Cut Line= 3
      1636254.99      6939688.02      1636005.00      6940138.00
      1636005.00      6940338.04
#Sta/Elev= 30
  4483.7 1658.52  4513.4 1657.66  4519.1 1656.92  4632.4 1651.24  4643.8 1650.32
  4654.1 1650.04  4689.6 1647.14  4757.1 1644.64  4784.5 1642.99  4849.7 1640.75
  4887.5 1638.01  4895.5 1636.97  4903.5 1638.67  4909.2 1637.87  4918.4 1639.08
  4941.3 1637.77  4952.7 1636.46  4984.7 1636.42  4989.2 1634.77  4989.7 1634.27
  5001.5 1634.27  5002.0 1634.77  5018.5 1635.35  5038.5 1640.40  5048.5 1642.38
  5068.5 1645.95  5118.5 1653.38  5138.5 1655.19  5168.5 1656.72  5198.5 1657.55
#Mann=3,-1,0
  4483.7    0.05       0  4989.2    0.05       0  5002.0    0.05       0
Bank Sta=4989.2,5002
Exp/Cntr=0.3,0.1

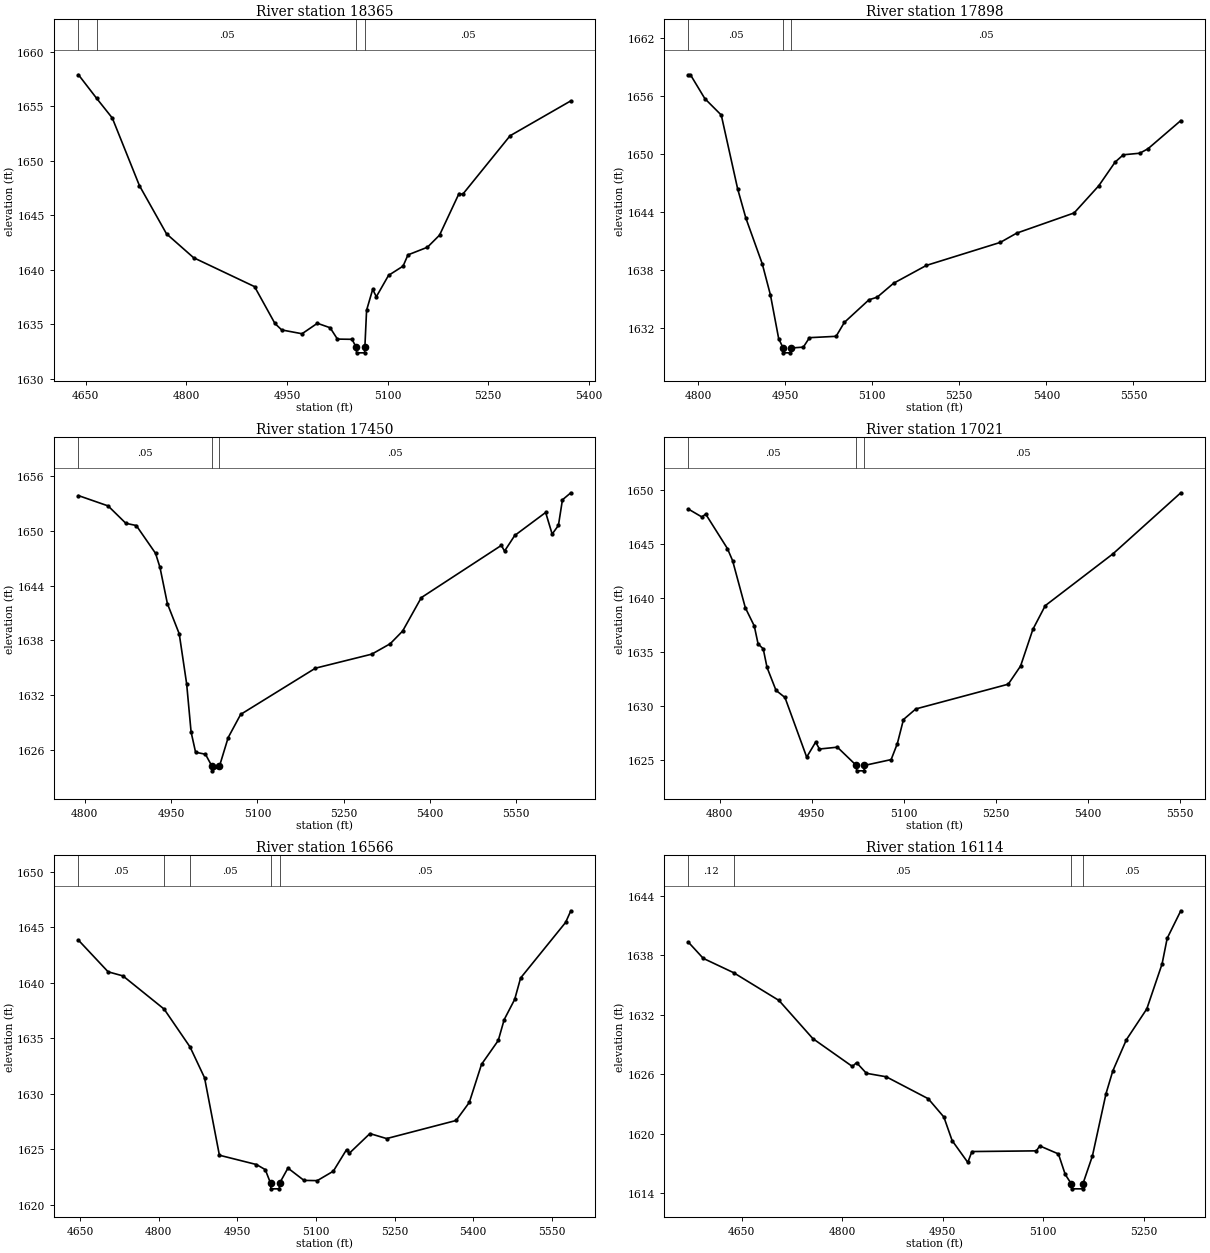
Type RM Length L Ch R = 1,18365,467,467,467
BEGIN DESCRIPTION:
Threemile Creek 31.0
END DESCRIPTION:
XS GIS Cut Line= 3
      1635555.00      6939587.99      1635605.00      6939938.00
      1635754.98      6940287.96
#Sta/Elev= 30
  4639.0 1657.87  4666.1 1655.71  4689.5 1653.90  4729.9 1647.71  4770.3 1643.29
  4810.7 1641.10  4901.6 1638.45  4932.0 1635.07  4942.1 1634.48  4972.4 1634.13
  4995.3 1635.09  5014.3 1634.68  5025.2 1633.64  5047.0 1633.62  5053.2 1632.88
  5053.7 1632.38  5065.6 1632.38  5066.1 1632.88  5068.7 1636.29  5077.8 1638.20
  5083.2 1637.52  5101.4 1639.48  5123.1 1640.33  5130.4 1641.36  5159.4 1642.06
  5177.5 1643.17  5206.5 1646.98  5212.0 1646.91  5282.7 1652.28  5373.3 1655.48
#Mann=4,-1,0
  4639.0    0.12       0  4666.1    0.05       0  5053.2    0.05       0
  5066.1    0.05       0
Bank Sta=5053.2,5066.1
Exp/Cntr=0.3,0.1

Type RM Length L Ch R = 1,17898,448,448,448
BEGIN DESCRIPTION:
Threemile Creek 30.0
END DESCRIPTION:
XS GIS Cut Line= 3
      1635005.01      6939738.01      1635155.00      6939888.00
      1635604.99      6940337.99
#Sta/Elev= 30
  4783.2 1658.21  4786.7 1658.21  4811.5 1655.74  4839.8 1654.04  4868.0 1646.41
  4882.2 1643.37  4910.5 1638.63  4924.6 1635.40  4938.7 1630.91  4946.4 1629.93
  4946.9 1629.43  4958.9 1629.43  4959.4 1629.93  4981.2 1630.02  4991.8 1631.00
  5037.7 1631.14  5051.9 1632.58  5094.3 1634.92  5108.5 1635.19  5136.7 1636.63
  5193.3 1638.48  5320.6 1640.86  5348.9 1641.82  5447.9 1643.91  5490.3 1646.72
  5518.6 1649.18  5532.7 1649.93  5561.0 1650.09  5575.1 1650.55  5631.7 1653.47
#Mann=3,-1,0
  4783.2    0.05       0  4946.4    0.05       0  4959.4    0.05       0
Bank Sta=4946.4,4959.4
Exp/Cntr=0.3,0.1

Type RM Length L Ch R = 1,17450,429,429,429
BEGIN DESCRIPTION:
Threemile Creek 29.0
END DESCRIPTION:
XS GIS Cut Line= 3
      1634705.01      6940188.00      1634905.00      6940238.00
      1635504.96      6940487.98
#Sta/Elev= 30
  4788.9 1653.87  4840.4 1652.74  4871.3 1650.83  4889.4 1650.59  4922.9 1647.54
  4930.6 1646.00  4943.5 1642.02  4964.1 1638.71  4977.0 1633.22  4984.7 1627.95
  4992.5 1625.72  5009.7 1625.50  5021.0 1624.18  5021.5 1623.68  5034.0 1624.18
  5049.2 1627.33  5070.9 1629.87  5200.9 1634.94  5298.9 1636.48  5330.9 1637.62
  5352.5 1639.01  5385.0 1642.68  5524.2 1648.41  5529.7 1647.78  5547.5 1649.50
  5601.2 1652.02  5612.5 1649.65  5623.4 1650.60  5630.4 1653.41  5645.0 1654.18
#Mann=3,-1,0
  4788.9    0.05       0  5021.0    0.05       0  5034.0    0.05       0
Bank Sta=5021,5034
Exp/Cntr=0.3,0.1

Type RM Length L Ch R = 1,17021,455,455,455
BEGIN DESCRIPTION:
Threemile Creek 28.0
END DESCRIPTION:
XS GIS Cut Line= 3
      1634655.00      6940438.00      1634805.00      6940638.00
      1635355.03      6940588.00
#Sta/Elev= 30
  4749.3 1648.23  4771.2 1647.50  4777.4 1647.77  4812.8 1644.58  4821.2 1643.47
  4842.0 1639.10  4856.6 1637.41  4862.8 1635.75  4871.2 1635.29  4877.4 1633.57
  4892.0 1631.45  4906.6 1630.79  4942.0 1625.27  4956.6 1626.66  4962.8 1626.02
  4992.0 1626.19  5022.9 1624.50  5023.4 1624.00  5035.5 1624.00  5036.0 1624.50
  5079.6 1625.04  5089.7 1626.52  5099.7 1628.75  5119.8 1629.73  5270.4 1632.02
  5290.5 1633.70  5310.6 1637.10  5330.7 1639.29  5441.1 1644.09  5551.6 1649.74
#Mann=3,-1,0
  4749.3    0.05       0  5022.9    0.05       0  5036.0    0.05       0
Bank Sta=5022.9,5036
Exp/Cntr=0.3,0.1

Type RM Length L Ch R = 1,16566,452,452,452
BEGIN DESCRIPTION:
Threemile Creek 27.0
END DESCRIPTION:
XS GIS Cut Line= 3
      1634405.02      6940788.02      1634655.00      6941038.00
      1635205.03      6941238.01
#Sta/Elev= 30
  4647.2 1643.84  4703.7 1640.99  4732.0 1640.62  4810.5 1637.63  4860.0 1634.21
  4887.6 1631.44  4915.9 1624.46  4986.6 1623.62  5003.4 1623.16  5013.5 1621.93
  5014.0 1621.43  5030.1 1621.43  5030.6 1621.93  5046.6 1623.30  5077.2 1622.19
  5102.5 1622.17  5133.1 1623.02  5158.3 1624.96  5163.7 1624.64  5202.9 1626.41
  5234.8 1625.96  5367.2 1627.59  5392.4 1629.22  5415.7 1632.65  5447.6 1634.80
  5458.9 1636.68  5478.9 1638.50  5490.2 1640.43  5576.0 1645.44  5586.0 1646.49
#Mann=5,-1,0
  4647.2    0.05       0  4810.5    0.12       0  4860.0    0.05       0
  5013.5    0.05       0  5030.6    0.05       0
Bank Sta=5013.5,5030.6
Exp/Cntr=0.3,0.1

Type RM Length L Ch R = 1,16114,436,436,436
BEGIN DESCRIPTION:
Threemile Creek 26.0
END DESCRIPTION:
XS GIS Cut Line= 3
      1634255.02      6941088.03      1634505.00      6941438.00
      1634555.00      6941737.98
#Sta/Elev= 30
  4570.8 1639.34  4592.9 1637.71  4638.2 1636.26  4705.9 1633.45  4756.3 1629.60
  4815.3 1626.78  4821.5 1627.17  4836.2 1626.09  4865.7 1625.74  4928.4 1623.52
  4951.7 1621.67  4964.0 1619.29  4987.4 1617.08  4993.5 1618.18  5089.6 1618.25
  5094.7 1618.75  5122.5 1617.94  5132.7 1615.86  5141.8 1614.91  5142.3 1614.41
  5158.5 1614.41  5159.0 1614.91  5173.2 1617.73  5193.5 1624.04  5203.6 1626.33
  5223.9 1629.49  5254.3 1632.60  5277.1 1637.15  5284.7 1639.74  5305.0 1642.52
#Mann=4,-1,0
  4570.8    0.12       0  4638.2    0.05       0  5141.8    0.05       0
  5159.0    0.05       0
Bank Sta=5141.8,5159
Exp/Cntr=0.3,0.1

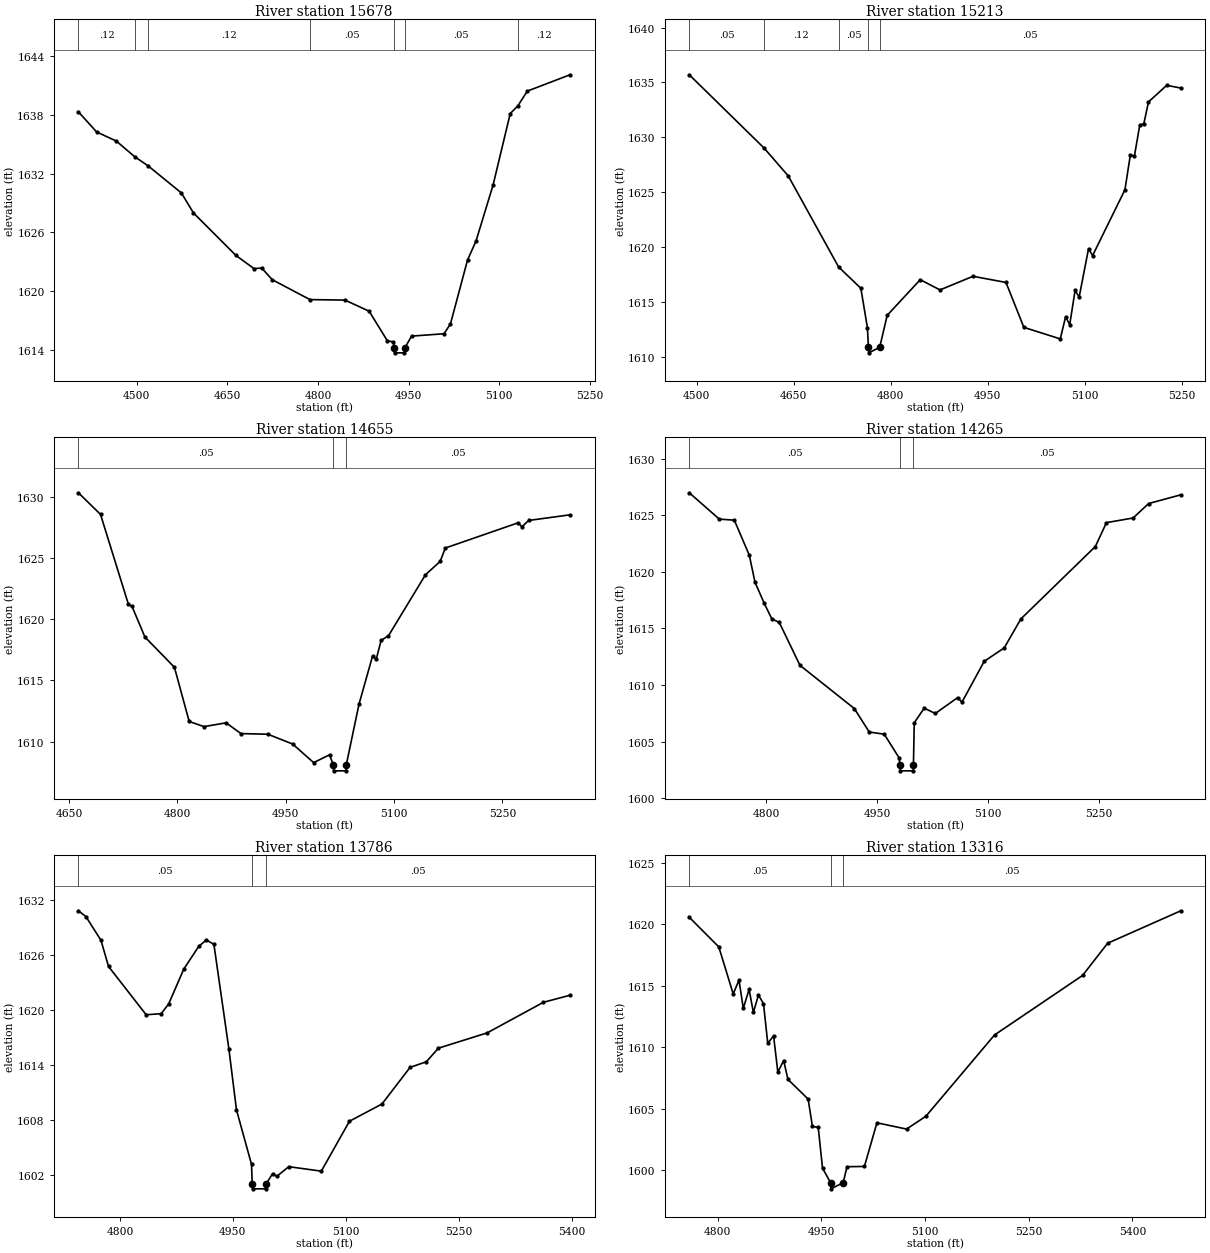
Type RM Length L Ch R = 1,15678,465,465,465
BEGIN DESCRIPTION:
Threemile Creek 25.0
END DESCRIPTION:
XS GIS Cut Line= 3
      1634155.00      6941138.04      1634205.00      6941738.00
      1634355.02      6941888.02
#Sta/Elev= 30
  4403.2 1638.31  4433.3 1636.26  4465.9 1635.33  4496.2 1633.74  4518.9 1632.78
  4573.7 1630.03  4593.8 1627.98  4664.1 1623.64  4694.2 1622.29  4706.7 1622.36
  4724.3 1621.16  4786.7 1619.13  4844.7 1619.08  4884.8 1617.94  4914.9 1614.92
  4925.0 1614.80  4926.3 1614.19  4926.8 1613.69  4943.2 1613.69  4943.7 1614.19
  4955.1 1615.40  5008.8 1615.64  5019.4 1616.64  5047.7 1623.17  5061.8 1625.12
  5090.1 1630.85  5118.4 1638.13  5131.2 1638.94  5146.7 1640.43  5217.4 1642.10
#Mann=7,-1,0
  4403.2    0.12       0  4496.2    0.05       0  4518.9    0.12       0
  4786.7    0.05       0  4926.3    0.05       0  4943.7    0.05       0
  5131.2    0.12       0
Bank Sta=4926.3,4943.7
Exp/Cntr=0.3,0.1

Type RM Length L Ch R = 1,15213,558,558,558
BEGIN DESCRIPTION:
Threemile Creek 24.0
END DESCRIPTION:
XS GIS Cut Line= 3
      1633855.01      6941187.95      1633755.00      6941688.00
      1633904.97      6941887.96
#Sta/Elev= 30
  4488.7 1635.70  4604.1 1629.04  4641.7 1626.49  4719.5 1618.20  4753.9 1616.26
  4764.1 1612.66  4765.6 1610.88  4766.1 1610.38  4783.0 1610.88  4794.7 1613.80
  4845.7 1617.04  4876.3 1616.11  4927.3 1617.35  4978.3 1616.79  5005.9 1612.70
  5062.2 1611.65  5070.5 1613.67  5076.8 1612.94  5085.1 1616.06  5091.4 1615.46
  5105.9 1619.86  5112.2 1619.24  5162.2 1625.23  5170.5 1628.39  5176.8 1628.29
  5185.1 1631.12  5191.4 1631.24  5198.6 1633.23  5226.8 1634.74  5248.6 1634.49
#Mann=5,-1,0
  4488.7    0.05       0  4604.1    0.12       0  4719.5    0.05       0
  4765.6    0.05       0  4783.0    0.05       0
Bank Sta=4765.6,4783
Exp/Cntr=0.3,0.1

Type RM Length L Ch R = 1,14655,390,390,390
BEGIN DESCRIPTION:
Threemile Creek 23.0
END DESCRIPTION:
XS GIS Cut Line= 3
      1633304.99      6941288.05      1633236.29      6941610.06
      1633165.78      6941954.05
#Sta/Elev= 30
  4663.1 1630.31  4693.7 1628.54  4732.2 1621.22  4737.3 1621.03  4755.1 1618.54
  4796.0 1616.06  4816.4 1611.64  4836.9 1611.22  4867.6 1611.53  4888.0 1610.65
  4925.2 1610.60  4959.6 1609.80  4988.7 1608.28  5010.7 1608.92  5015.8 1608.11
  5016.3 1607.61  5033.4 1607.61  5033.9 1608.11  5051.5 1613.06  5070.2 1616.97
  5075.3 1616.71  5082.1 1618.26  5092.3 1618.64  5143.4 1623.61  5163.8 1624.71
  5171.0 1625.80  5271.8 1627.86  5276.9 1627.53  5286.3 1628.05  5343.5 1628.51
#Mann=3,-1,0
  4663.1    0.05       0  5015.8    0.05       0  5033.9    0.05       0
Bank Sta=5015.8,5033.9
Exp/Cntr=0.3,0.1

Type RM Length L Ch R = 1,14265,479,479,479
BEGIN DESCRIPTION:
Threemile Creek 22.0
END DESCRIPTION:
XS GIS Cut Line= 3
      1632804.99      6941287.95      1632855.00      6941588.00
      1633054.98      6941887.97
#Sta/Elev= 30
  4696.3 1626.99  4736.9 1624.66  4757.2 1624.57  4777.5 1621.46  4785.1 1619.09
  4797.7 1617.21  4807.9 1615.84  4818.0 1615.53  4845.9 1611.74  4919.4 1607.92
  4939.7 1605.84  4959.9 1605.65  4980.2 1603.54  4981.2 1602.91  4981.7 1602.41
  4998.9 1602.41  4999.4 1602.91  5000.5 1606.66  5014.0 1607.95  5029.0 1607.48
  5059.1 1608.88  5065.1 1608.49  5095.1 1612.09  5122.2 1613.28  5144.7 1615.84
  5245.4 1622.24  5260.4 1624.35  5296.4 1624.76  5317.5 1626.04  5361.0 1626.81
#Mann=3,-1,0
  4696.3    0.05       0  4981.2    0.05       0  4999.4    0.05       0
Bank Sta=4981.2,4999.4
Exp/Cntr=0.3,0.1

Type RM Length L Ch R = 1,13786,470,470,470
BEGIN DESCRIPTION:
Threemile Creek 21.0
END DESCRIPTION:
XS GIS Cut Line= 3
      1632405.00      6941338.02      1632405.00      6941588.00
      1632605.00      6941938.00
#Sta/Elev= 30
  4744.8 1630.81  4754.8 1630.17  4774.8 1627.58  4784.8 1624.73  4834.8 1619.46
  4854.8 1619.58  4864.8 1620.66  4884.8 1624.45  4904.8 1626.94  4914.8 1627.62
  4924.8 1627.15  4944.8 1615.67  4954.8 1609.08  4974.8 1603.12  4975.7 1600.96
  4976.2 1600.46  4993.4 1600.46  4993.9 1600.96  5002.7 1602.11  5008.5 1601.83
  5024.3 1602.88  5067.5 1602.39  5104.9 1607.84  5148.1 1609.72  5185.5 1613.72
  5207.1 1614.33  5223.0 1615.81  5287.8 1617.48  5362.6 1620.82  5397.9 1621.59
#Mann=3,-1,0
  4744.8    0.05       0  4975.7    0.05       0  4993.9    0.05       0
Bank Sta=4975.7,4993.9
Exp/Cntr=0.3,0.1

Type RM Length L Ch R = 1,13316,440,440,440
BEGIN DESCRIPTION:
Threemile Creek 20.0
END DESCRIPTION:
XS GIS Cut Line= 3
      1631805.00      6941588.00      1632005.00      6941738.00
      1632305.02      6942088.02
#Sta/Elev= 30
  4759.0 1620.58  4801.7 1618.17  4822.5 1614.35  4830.9 1615.47  4837.1 1613.17
  4845.5 1614.72  4851.7 1612.84  4859.0 1614.26  4866.3 1613.56  4872.5 1610.33
  4880.9 1610.94  4887.1 1607.99  4895.5 1608.93  4901.7 1607.40  4930.9 1605.80
  4937.1 1603.57  4945.5 1603.50  4951.7 1600.18  4963.4 1599.00  4963.9 1598.50
  4981.6 1599.00  4987.1 1600.30  5012.3 1600.32  5030.4 1603.87  5073.2 1603.36
  5101.2 1604.40  5200.5 1611.01  5327.8 1615.85  5364.1 1618.47  5470.0 1621.11
#Mann=3,-1,0
  4759.0    0.05       0  4963.4    0.05       0  4981.6    0.05       0
Bank Sta=4963.4,4981.6
Exp/Cntr=0.3,0.1

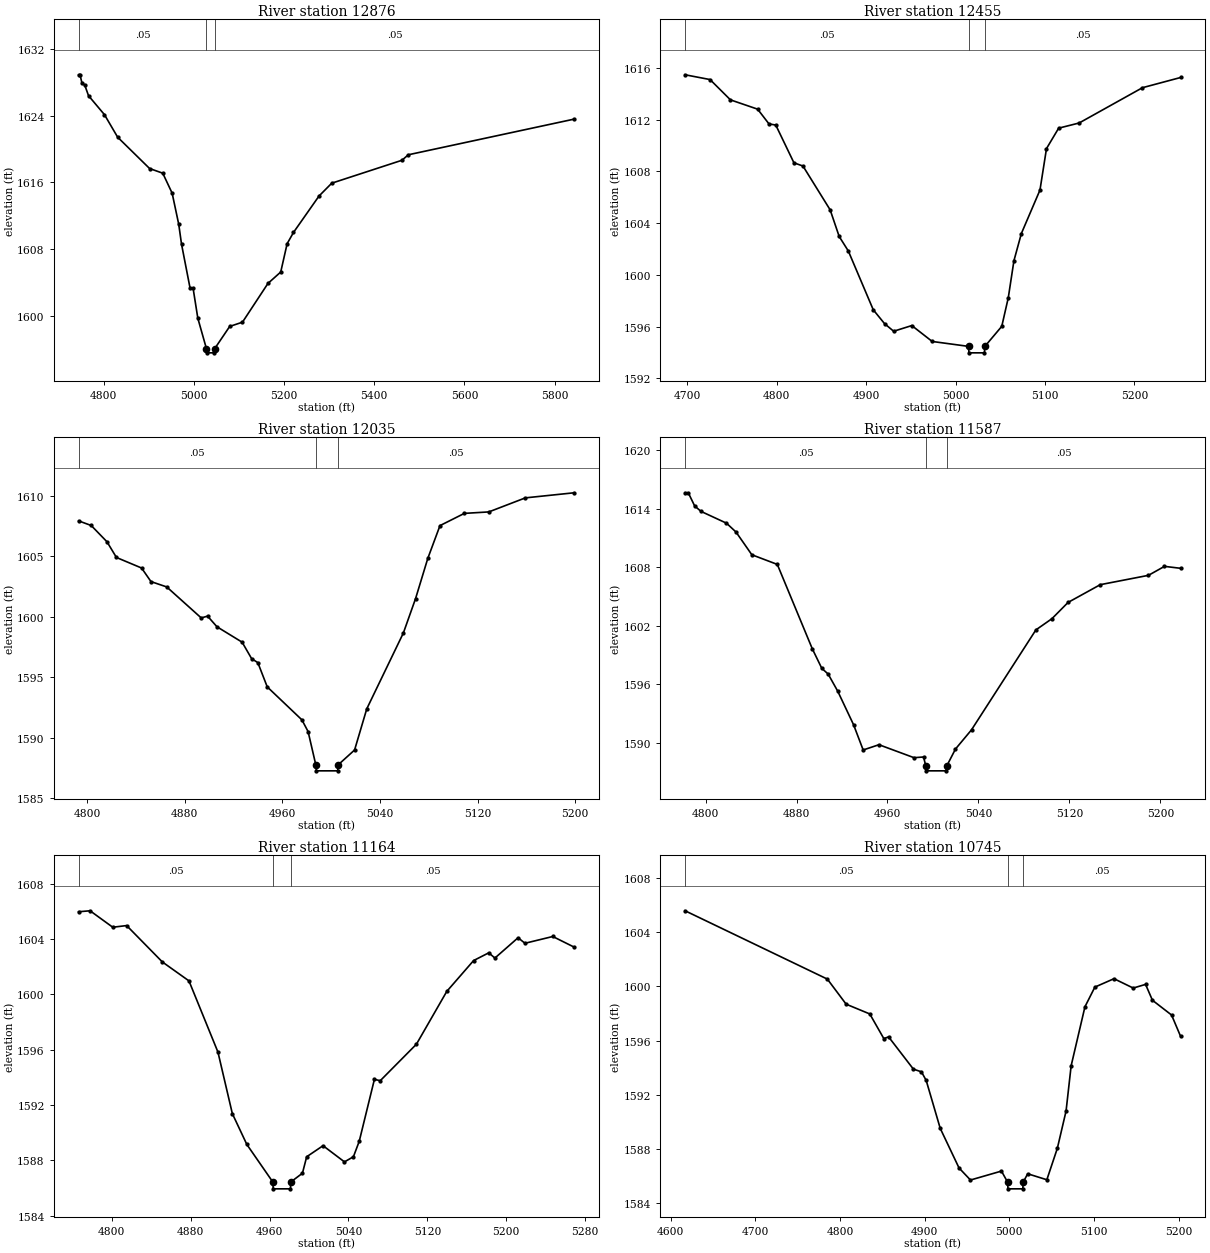
Type RM Length L Ch R = 1,12876,421,421,421
BEGIN DESCRIPTION:
Threemile Creek 19.0
END DESCRIPTION:
XS GIS Cut Line= 3
      1631504.99      6941787.98      1631655.00      6941988.00
      1632254.97      6942587.97
#Sta/Elev= 30
  4744.8 1628.91  4747.9 1628.91  4752.1 1627.93  4758.4 1627.67  4766.7 1626.40
  4802.1 1624.12  4831.3 1621.42  4902.1 1617.66  4931.3 1617.10  4952.1 1614.70
  4966.7 1610.97  4972.9 1608.58  4991.7 1603.34  4998.4 1603.34  5009.0 1599.70
  5028.1 1596.04  5028.6 1595.54  5045.9 1595.54  5046.4 1596.04  5079.7 1598.71
  5108.0 1599.22  5164.5 1603.87  5192.8 1605.24  5207.0 1608.64  5221.1 1609.99
  5277.7 1614.36  5305.9 1615.90  5461.5 1618.65  5475.7 1619.31  5843.3 1623.59
#Mann=3,-1,0
  4744.8    0.05       0  5028.1    0.05       0  5046.4    0.05       0
Bank Sta=5028.1,5046.4
Exp/Cntr=0.3,0.1

Type RM Length L Ch R = 1,12455,420,420,420
BEGIN DESCRIPTION:
Threemile Creek 18.0
END DESCRIPTION:
XS GIS Cut Line= 3
      1631405.00      6942038.00      1631455.00      6942338.00
      1631604.98      6942537.97
#Sta/Elev= 30
  4697.5 1615.48  4725.4 1615.11  4748.2 1613.54  4778.6 1612.82  4791.3 1611.68
  4798.9 1611.59  4819.2 1608.67  4829.3 1608.42  4859.7 1605.03  4869.8 1602.97
  4880.0 1601.85  4907.9 1597.30  4920.5 1596.23  4930.7 1595.64  4951.0 1596.08
  4973.8 1594.85  5014.4 1594.47  5014.9 1593.97  5032.2 1593.97  5032.7 1594.47
  5051.6 1596.02  5058.9 1598.24  5065.2 1601.10  5073.5 1603.20  5094.3 1606.56
  5101.6 1609.77  5115.2 1611.35  5138.1 1611.75  5208.9 1614.48  5251.6 1615.27
#Mann=3,-1,0
  4697.5    0.05       0  5014.4    0.05       0  5032.7    0.05       0
Bank Sta=5014.4,5032.7
Exp/Cntr=0.3,0.1

Type RM Length L Ch R = 1,12035,448,448,448
BEGIN DESCRIPTION:
Threemile Creek 17.0
END DESCRIPTION:
XS GIS Cut Line= 3
      1631054.99      6942337.97      1631105.00      6942538.00
      1631105.00      6942738.02
#Sta/Elev= 30
  4793.0 1607.91  4803.3 1607.53  4816.2 1606.19  4824.0 1604.89  4844.6 1604.02
  4852.3 1602.90  4865.2 1602.46  4893.5 1599.90  4898.7 1600.05  4906.4 1599.17
  4927.0 1597.90  4934.8 1596.54  4939.9 1596.21  4947.6 1594.21  4976.0 1591.49
  4981.1 1590.52  4987.4 1587.78  4987.9 1587.28  5005.3 1587.28  5005.8 1587.78
  5019.2 1589.00  5029.2 1592.40  5059.2 1598.66  5069.2 1601.50  5079.2 1604.81
  5089.2 1607.52  5109.2 1608.53  5129.2 1608.65  5159.2 1609.81  5199.2 1610.23
#Mann=3,-1,0
  4793.0    0.05       0  4987.4    0.05       0  5005.8    0.05       0
Bank Sta=4987.4,5005.8
Exp/Cntr=0.3,0.1

Type RM Length L Ch R = 1,11587,423,423,423
BEGIN DESCRIPTION:
Threemile Creek 16.0
END DESCRIPTION:
XS GIS Cut Line= 3
      1630604.98      6942487.96      1630705.00      6942688.00
      1630855.01      6942838.01
#Sta/Elev= 30
  4782.0 1615.64  4784.8 1615.64  4790.4 1614.29  4796.0 1613.73  4818.4 1612.52
  4826.8 1611.61  4840.7 1609.28  4863.1 1608.29  4893.8 1599.65  4902.2 1597.63
  4907.8 1597.04  4916.2 1595.29  4930.2 1591.83  4938.6 1589.25  4952.5 1589.79
  4983.3 1588.46  4991.7 1588.53  4993.7 1587.61  4994.2 1587.11  5011.6 1587.11
  5012.1 1587.61  5019.8 1589.35  5033.9 1591.32  5090.5 1601.57  5104.6 1602.72
  5118.8 1604.39  5147.1 1606.21  5189.5 1607.17  5203.6 1608.09  5217.8 1607.89
#Mann=3,-1,0
  4782.0    0.05       0  4993.7    0.05       0  5012.1    0.05       0
Bank Sta=4993.7,5012.1
Exp/Cntr=0.3,0.1

Type RM Length L Ch R = 1,11164,419,419,419
BEGIN DESCRIPTION:
Threemile Creek 15.0
END DESCRIPTION:
XS GIS Cut Line= 3
      1630216.97      6942698.62      1630355.00      6942888.00
      1630495.55      6943116.49
#Sta/Elev= 30
  4766.3 1605.98  4777.9 1606.05  4800.9 1604.86  4815.0 1604.98  4851.2 1602.35
  4878.2 1600.98  4907.6 1595.83  4922.2 1591.38  4936.9 1589.15  4963.2 1586.44
  4963.7 1585.94  4981.1 1585.94  4981.6 1586.44  4993.3 1587.07  4997.6 1588.26
  5014.2 1589.06  5035.9 1587.89  5045.0 1588.26  5050.9 1589.38  5066.3 1593.86
  5072.2 1593.76  5108.9 1596.40  5139.7 1600.22  5166.9 1602.45  5182.3 1603.01
  5188.5 1602.63  5212.0 1604.10  5219.0 1603.70  5247.2 1604.19  5268.9 1603.42
#Mann=3,-1,0
  4766.3    0.05       0  4963.2    0.03       0  4981.6    0.05       0
Bank Sta=4963.2,4981.6
Exp/Cntr=0.3,0.1

Type RM Length L Ch R = 1,10745,448,448,448
BEGIN DESCRIPTION:
Threemile Creek 14.0
END DESCRIPTION:
XS GIS Cut Line= 3
      1629831.26      6942747.92      1630005.00      6943088.00
      1630100.62      6943267.42
#Sta/Elev= 30
  4617.2 1605.57  4785.2 1600.53  4807.4 1598.68  4835.3 1597.96  4851.9 1596.14
  4857.5 1596.27  4886.8 1593.89  4896.3 1593.69  4901.9 1593.06  4918.5 1589.52
  4940.7 1586.60  4954.2 1585.71  4990.8 1586.37  4998.0 1585.56  4998.5 1585.06
  5016.0 1585.06  5016.5 1585.56  5021.8 1586.17  5044.4 1585.73  5056.8 1588.05
  5067.1 1590.80  5073.1 1594.14  5089.4 1598.49  5101.1 1599.94  5123.7 1600.56
  5146.4 1599.87  5161.0 1600.14  5169.1 1598.97  5191.7 1597.88  5202.4 1596.30
#Mann=3,-1,0
  4617.2    0.05       0  4998.0    0.03       0  5016.5    0.05       0
Bank Sta=4998,5016.5
Exp/Cntr=0.3,0.1

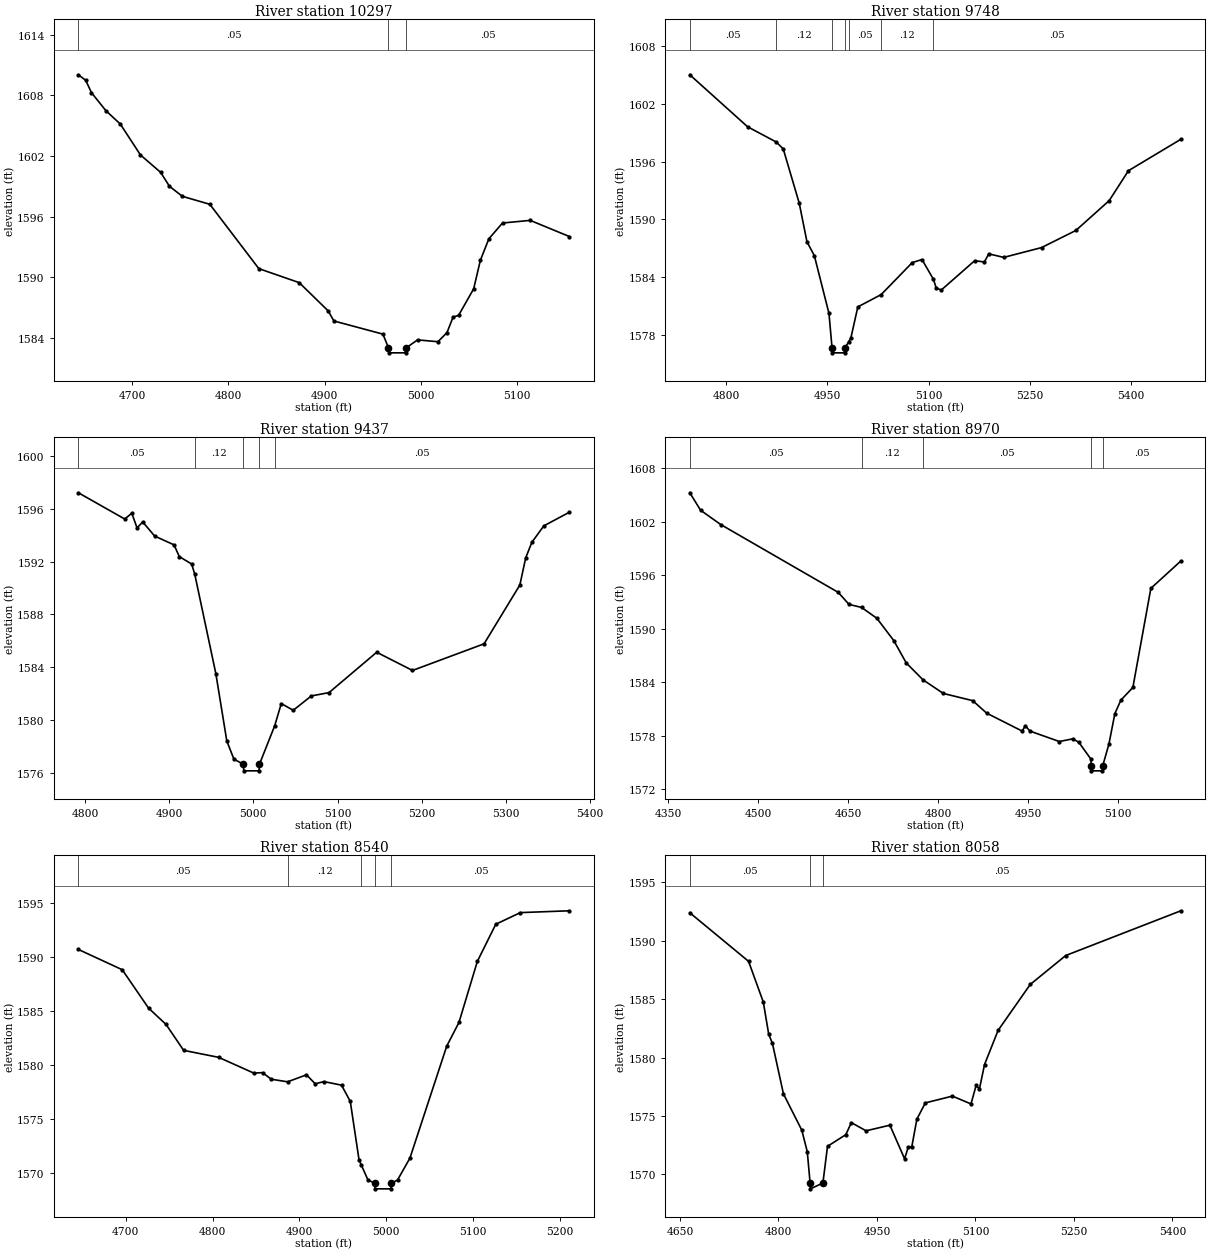
Type RM Length L Ch R = 1,10297,549,549,549
BEGIN DESCRIPTION:
Threemile Creek 13.0
END DESCRIPTION:
XS GIS Cut Line= 3
      1629404.98      6942937.96      1629605.00      6943238.00
      1629680.62      6943368.24
#Sta/Elev= 30
  4643.8 1610.03  4651.4 1609.48  4657.4 1608.26  4672.4 1606.48  4687.4 1605.16
  4708.4 1602.10  4729.5 1600.37  4738.5 1599.01  4752.0 1598.01  4780.6 1597.22
  4831.6 1590.86  4873.7 1589.47  4903.7 1586.69  4909.8 1585.68  4960.8 1584.38
  4966.6 1583.03  4967.1 1582.53  4984.6 1582.53  4985.1 1583.03  4996.9 1583.81
  5018.1 1583.63  5027.5 1584.53  5033.8 1586.06  5039.6 1586.24  5055.3 1588.87
  5062.2 1591.67  5071.1 1593.81  5085.3 1595.37  5114.1 1595.63  5155.0 1594.03
#Mann=3,-1,0
  4643.8    0.05       0  4966.6    0.03       0  4985.1    0.05       0
Bank Sta=4966.6,4985.1
Exp/Cntr=0.3,0.1

Type RM Length L Ch R = 1,9748,311,311,311
BEGIN DESCRIPTION:
Threemile Creek 12.0
END DESCRIPTION:
XS GIS Cut Line= 3
      1629054.99      6943237.98      1629153.85      6943471.96
      1629455.00      6943838.00
#Sta/Elev= 30
  4746.0 1605.04  4831.7 1599.63  4874.0 1598.05  4884.5 1597.33  4908.2 1591.69
  4919.7 1587.66  4930.6 1586.23  4952.3 1580.22  4956.9 1576.61  4957.4 1576.11
  4975.5 1576.11  4976.0 1576.61  4981.4 1577.25  4984.8 1577.66  4995.1 1580.89
  5029.7 1582.17  5075.8 1585.50  5090.2 1585.82  5107.2 1583.76  5111.4 1582.84
  5118.9 1582.65  5168.4 1585.70  5182.7 1585.56  5189.2 1586.41  5211.4 1586.04
  5267.4 1587.06  5318.3 1588.84  5367.8 1591.95  5396.3 1595.06  5474.0 1598.33
#Mann=7,-1,0
  4746.0    0.05       0  4874.0    0.12       0  4956.9    0.05       0
  4976.0    0.12       0  4981.4    0.05       0  5029.7    0.12       0
  5107.2    0.05       0
Bank Sta=4956.9,4976
Exp/Cntr=0.3,0.1

Type RM Length L Ch R = 1,9437,467,467,467
BEGIN DESCRIPTION:
Threemile Creek 11.0
END DESCRIPTION:
XS GIS Cut Line= 3
      1628783.36      6943562.19      1628955.00      6943688.00
      1629207.70      6943958.66
#Sta/Elev= 30
  4792.3 1597.21  4847.3 1595.22  4855.7 1595.66  4861.9 1594.55  4868.7 1595.00
  4882.8 1593.93  4905.9 1593.26  4912.1 1592.37  4926.8 1591.81  4930.4 1591.05
  4955.5 1583.50  4968.5 1578.40  4976.9 1577.02  4988.2 1576.63  4988.7 1576.13
  5006.8 1576.13  5007.3 1576.63  5025.4 1579.55  5033.2 1581.23  5047.4 1580.72
  5068.9 1581.81  5089.9 1582.06  5146.5 1585.12  5189.0 1583.74  5274.0 1585.76
  5316.5 1590.22  5323.4 1592.27  5330.7 1593.45  5344.9 1594.70  5375.4 1595.74
#Mann=5,-1,0
  4792.3    0.05       0  4930.4    0.12       0  4988.2    0.07       0
  5007.3    0.12       0  5025.4    0.05       0
Bank Sta=4988.2,5007.3
Exp/Cntr=0.3,0.1

Type RM Length L Ch R = 1,8970,430,430,430
BEGIN DESCRIPTION:
Threemile Creek 10.0
END DESCRIPTION:
XS GIS Cut Line= 3
      1628505.00      6943438.01      1628655.00      6944038.00
      1628655.00      6944238.04
#Sta/Elev= 30
  4386.0 1605.24  4404.0 1603.28  4437.5 1601.68  4633.4 1594.07  4651.4 1592.72
  4672.3 1592.38  4697.8 1591.16  4726.1 1588.65  4746.8 1586.15  4774.7 1584.26
  4808.6 1582.73  4857.6 1581.92  4880.8 1580.52  4940.0 1578.51  4945.2 1579.11
  4952.9 1578.51  5001.9 1577.34  5024.5 1577.64  5034.5 1577.25  5054.5 1575.37
  5054.9 1574.55  5055.4 1574.05  5073.5 1574.05  5074.0 1574.55  5084.5 1577.03
  5094.5 1580.47  5104.5 1581.98  5124.5 1583.40  5154.5 1594.52  5204.5 1597.59
#Mann=5,-1,0
  4386.0    0.05       0  4672.3    0.12       0  4774.7    0.05       0
  5054.9    0.05       0  5074.0    0.05       0
Bank Sta=5054.9,5074
Exp/Cntr=0.3,0.1

Type RM Length L Ch R = 1,8540,482,482,482
BEGIN DESCRIPTION:
Threemile Creek 9.0
END DESCRIPTION:
XS GIS Cut Line= 3
      1628205.00      6943787.99      1628255.00      6944138.00
      1628405.00      6944288.00
#Sta/Elev= 30
  4645.4 1590.73  4695.9 1588.85  4726.2 1585.29  4746.4 1583.77  4766.6 1581.37
  4807.0 1580.72  4847.4 1579.26  4857.5 1579.30  4867.6 1578.69  4886.4 1578.45
  4908.1 1579.10  4918.2 1578.27  4928.3 1578.47  4948.5 1578.14  4958.6 1576.63
  4968.7 1571.20  4971.3 1570.73  4978.8 1569.37  4986.8 1569.02  4987.3 1568.52
  5005.5 1568.52  5006.0 1569.02  5013.1 1569.35  5027.3 1571.37  5069.7 1581.76
  5083.8 1583.96  5105.0 1589.63  5126.2 1593.07  5154.5 1594.15  5211.1 1594.32
#Mann=5,-1,0
  4645.4    0.05       0  4886.4    0.12       0  4971.3    0.05       0
  4986.8    0.05       0  5006.0    0.05       0
Bank Sta=4986.8,5006
Exp/Cntr=0.3,0.1

Type RM Length L Ch R = 1,8058,482,482,482
BEGIN DESCRIPTION:
Threemile Creek 8.0
END DESCRIPTION:
XS GIS Cut Line= 3
      1627654.98      6943937.96      1627805.00      6944238.00
      1627905.01      6944638.03
#Sta/Elev= 30
  4665.1 1592.40  4754.6 1588.24  4777.0 1584.76  4785.3 1581.99  4790.9 1581.22
  4807.7 1576.89  4835.6 1573.79  4844.0 1571.94  4848.3 1569.26  4848.8 1568.76
  4867.8 1569.26  4874.8 1572.40  4902.7 1573.40  4911.1 1574.43  4933.5 1573.73
  4969.8 1574.21  4992.2 1571.33  4997.8 1572.34  5003.1 1572.34  5010.9 1574.73
  5023.8 1576.12  5065.0 1576.70  5093.3 1576.03  5101.1 1577.61  5106.2 1577.32
  5113.9 1579.40  5134.6 1582.33  5183.5 1586.26  5237.6 1588.74  5412.9 1592.57
#Mann=3,-1,0
  4665.1    0.05       0  4848.3    0.03       0  4867.8    0.05       0
Bank Sta=4848.3,4867.8
Exp/Cntr=0.3,0.1