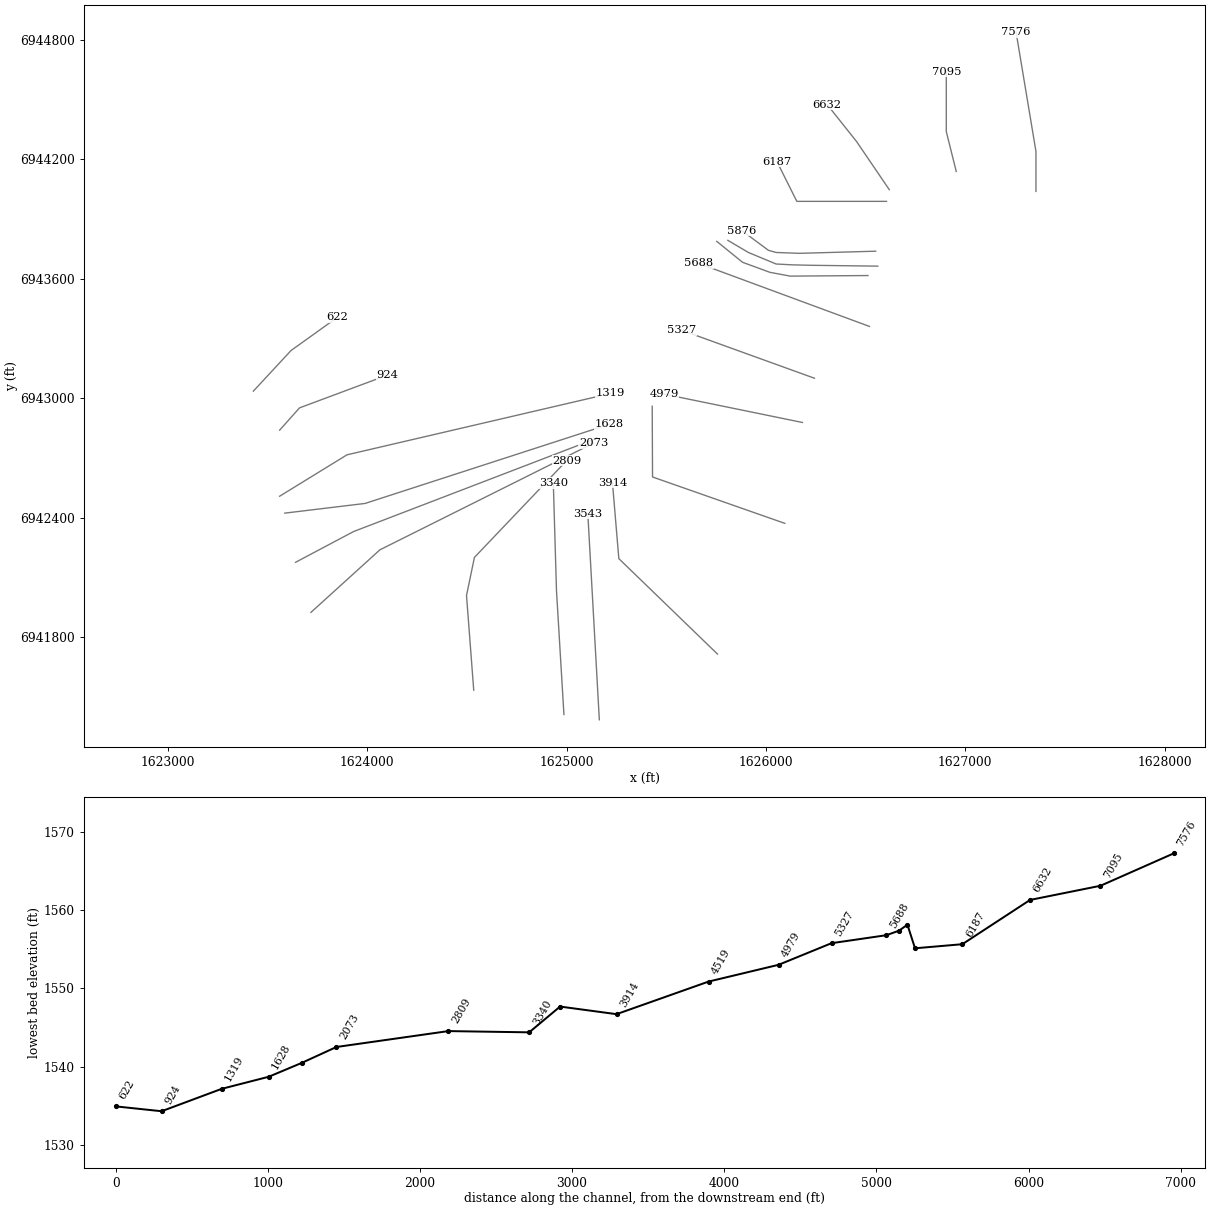
HEC-RAS study Threemile Creek.prj: Threemile Creek Base Level Engineering

--- Threemile Creek.g01 (geometry) --- (continued)

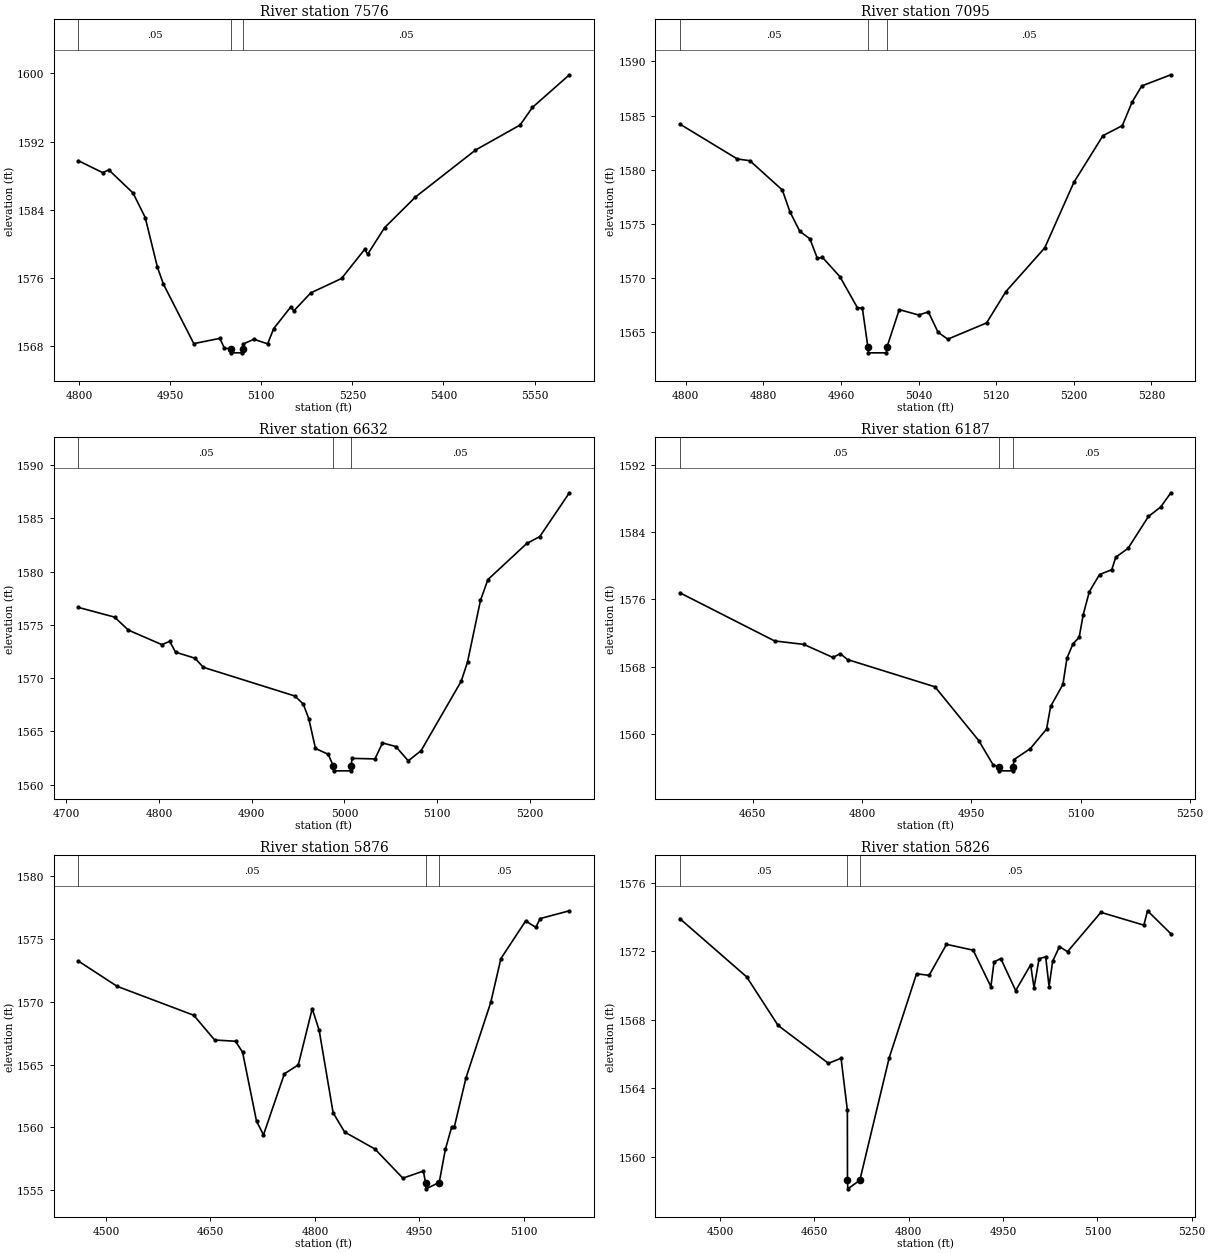
Type RM Length L Ch R = 1,7576,481,481,481
BEGIN DESCRIPTION:
Threemile Creek 7.0
END DESCRIPTION:
XS GIS Cut Line= 3
      1627355.00      6944038.02      1627355.00      6944238.00
      1627254.99      6944838.04
#Sta/Elev= 30
  4799.0 1589.76  4839.0 1588.36  4849.0 1588.69  4889.0 1585.97  4909.0 1583.10
  4929.0 1577.29  4939.0 1575.28  4989.0 1568.31  5031.9 1568.93  5039.5 1567.75
  5050.1 1567.73  5050.6 1567.23  5069.1 1567.23  5069.6 1567.73  5069.9 1568.25
  5087.7 1568.82  5110.5 1568.29  5120.6 1570.08  5148.5 1572.60  5153.6 1572.15
  5181.5 1574.26  5232.2 1575.95  5270.2 1579.36  5275.2 1578.80  5303.1 1581.91
  5353.8 1585.50  5452.7 1591.01  5526.2 1593.95  5546.4 1596.01  5607.3 1599.84
#Mann=3,-1,0
  4799.0    0.05       0  5050.1    0.05       0  5069.6    0.05       0
Bank Sta=5050.1,5069.6
Exp/Cntr=0.3,0.1

Type RM Length L Ch R = 1,7095,463,463,463
BEGIN DESCRIPTION:
Threemile Creek 6.0
END DESCRIPTION:
XS GIS Cut Line= 3
      1626955.01      6944137.96      1626905.00      6944338.00
      1626905.00      6944638.01
#Sta/Elev= 30
  4793.9 1584.21  4853.2 1580.99  4866.1 1580.83  4899.6 1578.12  4907.3 1576.13
  4917.6 1574.31  4927.9 1573.63  4935.7 1571.81  4940.8 1571.92  4958.9 1570.13
  4976.9 1567.27  4982.1 1567.21  4987.8 1563.60  4988.3 1563.10  5006.8 1563.10
  5007.3 1563.60  5020.1 1567.09  5040.1 1566.59  5050.1 1566.88  5060.1 1565.00
  5070.1 1564.36  5110.1 1565.86  5130.1 1568.76  5170.1 1572.79  5200.1 1578.83
  5230.1 1583.14  5250.1 1584.07  5260.1 1586.23  5270.1 1587.73  5300.1 1588.76
#Mann=3,-1,0
  4793.9    0.05       0  4987.8    0.03       0  5007.3    0.05       0
Bank Sta=4987.8,5007.3
Exp/Cntr=0.3,0.1

Type RM Length L Ch R = 1,6632,445,445,445
BEGIN DESCRIPTION:
Threemile Creek 5.0
END DESCRIPTION:
XS GIS Cut Line= 3
      1626619.07      6944046.55      1626455.00      6944288.00
      1626307.07      6944474.03
#Sta/Elev= 30
  4713.0 1576.63  4752.0 1575.72  4766.9 1574.50  4802.9 1573.14  4811.5 1573.44
  4817.8 1572.43  4838.8 1571.86  4847.7 1571.01  4946.6 1568.31  4955.5 1567.56
  4961.5 1566.19  4968.7 1563.39  4982.5 1562.84  4987.7 1561.79  4988.2 1561.29
  5006.8 1561.29  5007.3 1561.79  5008.1 1562.46  5032.9 1562.41  5041.0 1563.91
  5055.4 1563.57  5068.8 1562.23  5082.6 1563.18  5125.9 1569.70  5132.7 1571.50
  5146.7 1577.29  5154.7 1579.24  5196.6 1582.63  5210.7 1583.28  5242.6 1587.39
#Mann=3,-1,0
  4713.0    0.05       0  4987.7    0.05       0  5007.3    0.05       0
Bank Sta=4987.7,5007.3
Exp/Cntr=0.3,0.1

Type RM Length L Ch R = 1,6187,311,311,311
BEGIN DESCRIPTION:
Threemile Creek 4.0
END DESCRIPTION:
XS GIS Cut Line= 3
      1626604.99      6943988.00      1626155.00      6943988.00
      1626055.00      6944188.00
#Sta/Elev= 30
  4550.1 1576.79  4680.1 1571.07  4720.1 1570.66  4760.1 1569.11  4770.1 1569.56
  4780.1 1568.86  4900.1 1565.62  4960.1 1559.24  4980.1 1556.32  4987.8 1556.14
  4988.3 1555.64  5006.9 1555.64  5007.4 1556.14  5008.5 1556.98  5030.8 1558.27
  5053.2 1560.60  5058.8 1563.30  5075.6 1565.90  5081.2 1569.04  5089.5 1570.73
  5097.9 1571.50  5103.5 1574.20  5111.9 1576.93  5125.9 1578.96  5142.6 1579.53
  5148.2 1581.02  5165.0 1582.07  5193.0 1585.86  5209.7 1586.97  5223.7 1588.67
#Mann=3,-1,0
  4550.1    0.05       0  4987.8    0.05       0  5007.4    0.05       0
Bank Sta=4987.8,5007.4
Exp/Cntr=0.3,0.1

Type RM Length L Ch R = 1,5876,50,50,50
BEGIN DESCRIPTION:
Mapping XS 9ef67ae2
END DESCRIPTION:
XS GIS Cut Line= 5
      1626550.56      6943737.93      1626166.95      6943727.22
      1626051.24      6943731.51      1626012.66      6943742.22
      1625879.90      6943840.72
#Sta/Elev= 30
  4460.4 1573.24  4516.0 1571.23  4626.0 1568.93  4656.0 1566.96  4686.0 1566.86
  4696.1 1565.99  4716.1 1560.51  4726.1 1559.41  4756.1 1564.27  4776.1 1564.98
  4796.1 1569.45  4806.1 1567.72  4826.1 1561.17  4842.6 1559.64  4886.1 1558.29
  4926.2 1555.97  4955.6 1556.53  4958.8 1555.62  4959.3 1555.12  4978.4 1555.62
  4987.2 1558.25  4996.2 1560.02  5000.0 1560.02  5016.9 1563.96  5052.4 1569.95
  5067.0 1573.44  5102.5 1576.43  5117.1 1575.92  5123.3 1576.62  5165.3 1577.24
#Mann=3,-1,0
  4460.4    0.05       0  4958.8    0.05       0  4978.4    0.05       0
Bank Sta=4958.8,4978.4
Exp/Cntr=0.3,0.1

Type RM Length L Ch R = 1,5826,55,55,55
BEGIN DESCRIPTION:
Mapping XS 1ace57e0
END DESCRIPTION:
XS GIS Cut Line= 6
      1626561.24      6943662.93      1626226.95      6943667.22
      1626134.81      6943669.36      1626051.24      6943673.65
      1625911.95      6943731.51      1625809.01      6943792.43
#Sta/Elev= 30
  4436.2 1573.91  4542.4 1570.51  4592.4 1567.67  4672.5 1565.46  4692.5 1565.76
  4702.5 1562.72  4702.7 1558.63  4703.2 1558.13  4722.3 1558.63  4769.0 1565.78
  4812.5 1570.69  4832.5 1570.60  4860.1 1572.41  4902.5 1572.07  4930.7 1569.94
  4935.7 1571.38  4946.4 1571.58  4970.1 1569.71  4993.9 1571.21  4999.3 1569.87
  5007.3 1571.57  5017.8 1571.68  5023.2 1569.94  5028.9 1571.42  5039.7 1572.28
  5052.5 1571.98  5105.6 1574.28  5173.9 1573.53  5179.7 1574.37  5216.8 1573.03
#Mann=3,-1,0
  4436.2    0.05       0  4702.7    0.05       0  4722.3    0.05       0
Bank Sta=4702.7,4722.3
Exp/Cntr=0.3,0.1

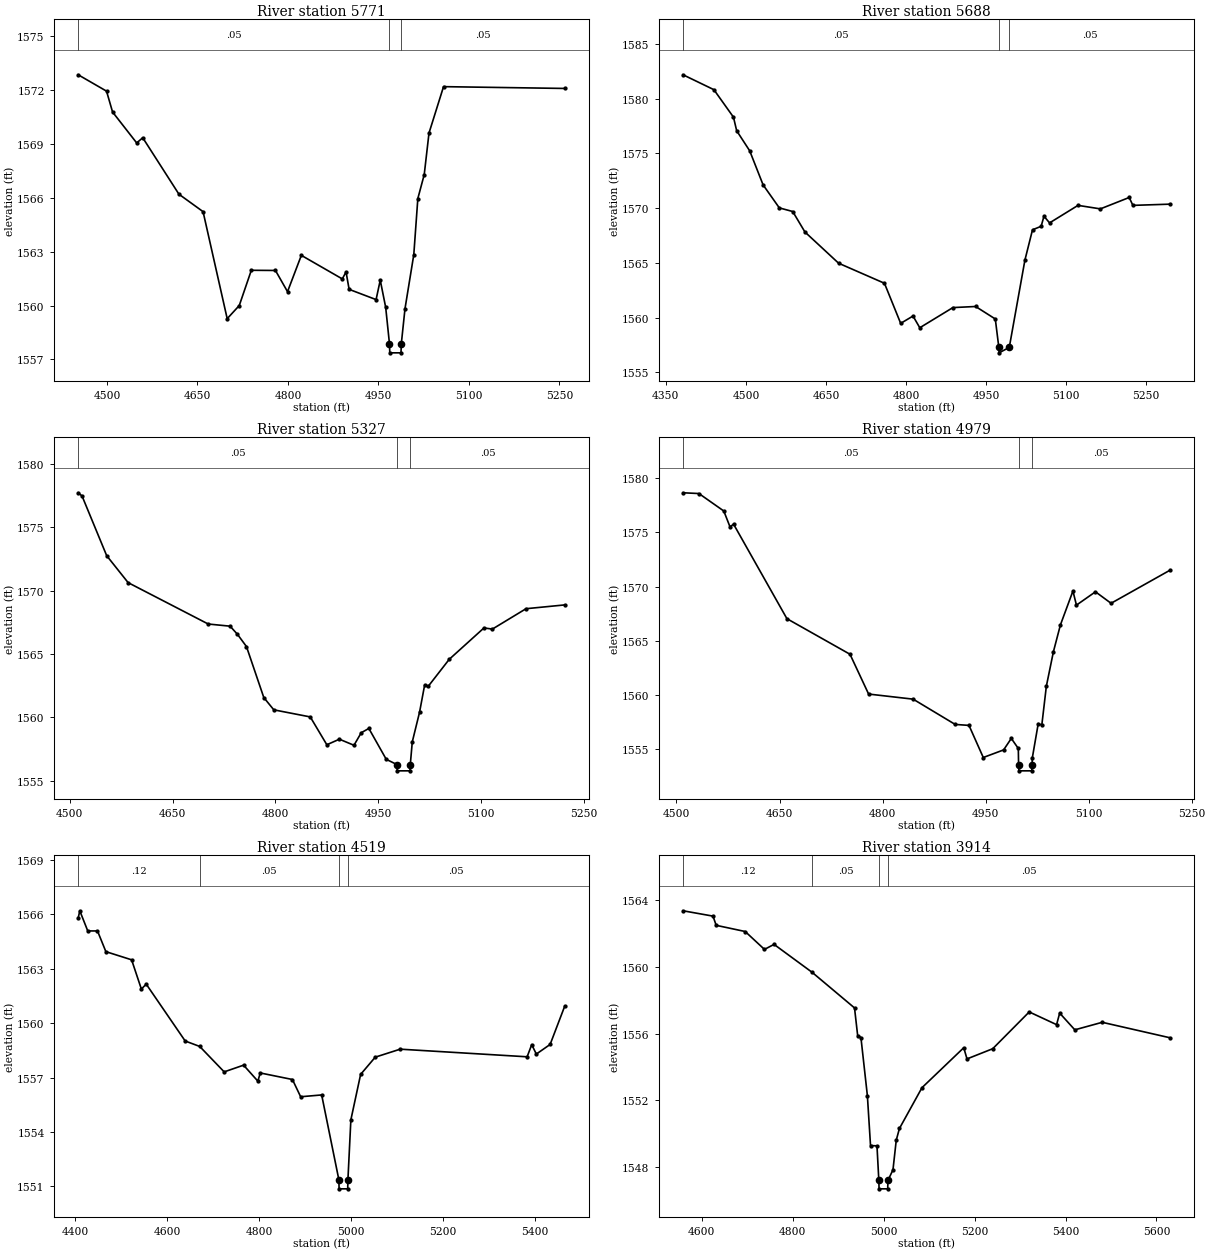
Type RM Length L Ch R = 1,5771,83,83,83
BEGIN DESCRIPTION:
Mapping XS d0a87114
END DESCRIPTION:
XS GIS Cut Line= 5
      1626511.96      6943615.79      1626122.31      6943612.83
      1626019.88      6943631.93      1625882.72      6943682.28
      1625753.39      6943787.21
#Sta/Elev= 30
  4452.3 1572.83  4499.3 1571.92  4509.3 1570.76  4549.3 1569.04  4559.3 1569.33
  4619.3 1566.19  4659.3 1565.22  4699.3 1559.27  4719.3 1560.00  4739.3 1561.96
  4779.3 1561.95  4799.3 1560.77  4822.2 1562.79  4890.1 1561.48  4896.3 1561.87
  4901.4 1560.90  4946.1 1560.33  4953.0 1561.41  4962.0 1559.90  4968.3 1557.87
  4968.8 1557.37  4987.4 1557.37  4987.9 1557.87  4994.0 1559.82  5008.6 1562.83
  5015.3 1565.95  5025.9 1567.28  5033.8 1569.59  5057.9 1572.17  5258.8 1572.07
#Mann=3,-1,0
  4452.3    0.05       0  4968.3    0.03       0  4987.9    0.05       0
Bank Sta=4968.3,4987.9
Exp/Cntr=0.3,0.1

Type RM Length L Ch R = 1,5688,361,361,361
BEGIN DESCRIPTION:
Mapping XS 84c13224
END DESCRIPTION:
XS GIS Cut Line= 2
      1626519.26      6943360.51      1625664.00      6943676.30
#Sta/Elev= 30
  4382.2 1582.17  4440.0 1580.81  4476.7 1578.30  4482.7 1577.06  4507.1 1575.23
  4532.2 1572.12  4562.6 1570.02  4587.7 1569.69  4610.6 1567.82  4673.7 1564.97
  4759.6 1563.14  4790.0 1559.48  4813.1 1560.15  4825.8 1559.08  4887.8 1560.92
  4930.4 1561.02  4967.3 1559.88  4973.9 1557.29  4974.4 1556.79  4993.5 1557.29
  5022.8 1565.26  5037.0 1568.02  5053.2 1568.34  5058.5 1569.26  5069.0 1568.65
  5122.3 1570.25  5164.2 1569.93  5218.2 1570.97  5225.1 1570.25  5293.9 1570.36
#Mann=3,-1,0
  4382.2    0.05       0  4973.9    0.03       0  4993.5    0.05       0
Bank Sta=4973.9,4993.5
Exp/Cntr=0.3,0.1

Type RM Length L Ch R = 1,5327,348,348,348
BEGIN DESCRIPTION:
Mapping XS b4b541eb
END DESCRIPTION:
XS GIS Cut Line= 2
      1626243.53      6943100.44      1625575.71      6943341.82
#Sta/Elev= 30
  4512.3 1577.74  4517.9 1577.49  4553.9 1572.77  4585.2 1570.64  4702.1 1567.37
  4734.0 1567.20  4744.7 1566.56  4757.9 1565.59  4783.2 1561.56  4797.8 1560.59
  4851.0 1560.03  4875.2 1557.83  4893.5 1558.27  4914.8 1557.79  4925.4 1558.78
  4936.5 1559.12  4961.9 1556.68  4977.4 1556.27  4977.9 1555.77  4996.5 1555.77
  4997.0 1556.27  4999.9 1558.06  5010.5 1560.40  5017.9 1562.54  5023.2 1562.45
  5053.8 1564.58  5104.5 1567.06  5116.8 1566.97  5165.9 1568.58  5222.4 1568.88
#Mann=3,-1,0
  4512.3    0.05       0  4977.4    0.03       0  4997.0    0.05       0
Bank Sta=4977.4,4997
Exp/Cntr=0.3,0.1

Type RM Length L Ch R = 1,4979,460,460,460
BEGIN DESCRIPTION:
Mapping XS 2fcef9f5
END DESCRIPTION:
XS GIS Cut Line= 2
      1626183.07      6942878.46      1625489.30      6943020.68
#Sta/Elev= 30
  4509.6 1578.65  4532.7 1578.58  4568.9 1576.97  4578.0 1575.50  4583.1 1575.76
  4660.8 1567.04  4752.6 1563.76  4779.7 1560.09  4844.5 1559.62  4905.7 1557.29
  4925.8 1557.20  4946.6 1554.24  4976.2 1554.94  4987.4 1556.00  4997.6 1555.07
  4998.0 1553.51  4998.5 1553.01  5017.1 1553.01  5017.6 1553.51  5018.0 1554.21
  5026.6 1557.37  5031.8 1557.23  5038.4 1560.81  5048.7 1564.00  5058.9 1566.47
  5077.1 1569.59  5082.2 1568.29  5109.9 1569.52  5132.6 1568.46  5217.8 1571.49
#Mann=3,-1,0
  4509.6    0.05       0  4998.0    0.03       0  5017.6    0.05       0
Bank Sta=4998,5017.6
Exp/Cntr=0.3,0.1

Type RM Length L Ch R = 1,4519,605,605,605
BEGIN DESCRIPTION:
Mapping XS 8c6a00e8
END DESCRIPTION:
XS GIS Cut Line= 3
      1626094.64      6942372.29      1625430.99      6942604.95
      1625429.35      6942959.80
#Sta/Elev= 30
  4406.6 1565.78  4410.1 1566.18  4427.4 1565.07  4448.6 1565.07  4466.8 1563.93
  4522.8 1563.48  4544.0 1561.87  4554.6 1562.14  4639.3 1559.01  4670.9 1558.71
  4724.1 1557.31  4766.3 1557.68  4797.3 1556.80  4802.6 1557.25  4872.5 1556.89
  4890.4 1555.94  4936.1 1556.04  4973.5 1551.37  4974.0 1550.87  4992.7 1550.87
  4993.2 1551.37  4999.6 1554.67  5020.8 1557.17  5052.6 1558.12  5106.9 1558.56
  5382.9 1558.14  5392.9 1558.81  5402.9 1558.29  5432.9 1558.82  5464.7 1560.93
#Mann=4,-1,0
  4406.6    0.12       0  4670.9    0.05       0  4973.5    0.03       0
  4993.2    0.05       0
Bank Sta=4973.5,4993.2
Exp/Cntr=0.3,0.1

Type RM Length L Ch R = 1,3914,371,371,371
BEGIN DESCRIPTION:
Mapping XS 2f310678
END DESCRIPTION:
XS GIS Cut Line= 3
      1625756.73      6941716.54      1625261.90      6942195.28
      1625229.86      6942575.72
#Sta/Elev= 30
  4558.6 1563.34  4624.5 1563.02  4631.5 1562.47  4695.3 1562.10  4737.7 1561.03
  4758.8 1561.33  4842.5 1559.66  4935.8 1557.53  4942.7 1555.88  4949.9 1555.76
  4964.1 1552.28  4971.0 1549.30  4985.2 1549.28  4989.3 1547.21  4989.8 1546.71
  5008.8 1546.71  5009.3 1547.21  5020.4 1547.85  5027.6 1549.62  5034.6 1550.32
  5084.2 1552.76  5176.1 1555.15  5183.2 1554.48  5239.8 1555.09  5320.1 1557.29
  5380.3 1556.53  5387.1 1557.22  5420.4 1556.22  5480.7 1556.67  5628.9 1555.75
#Mann=4,-1,0
  4558.6    0.12       0  4842.5    0.05       0  4989.3    0.03       0
  5009.3    0.05       0
Bank Sta=4989.3,5009.3
Exp/Cntr=0.3,0.1

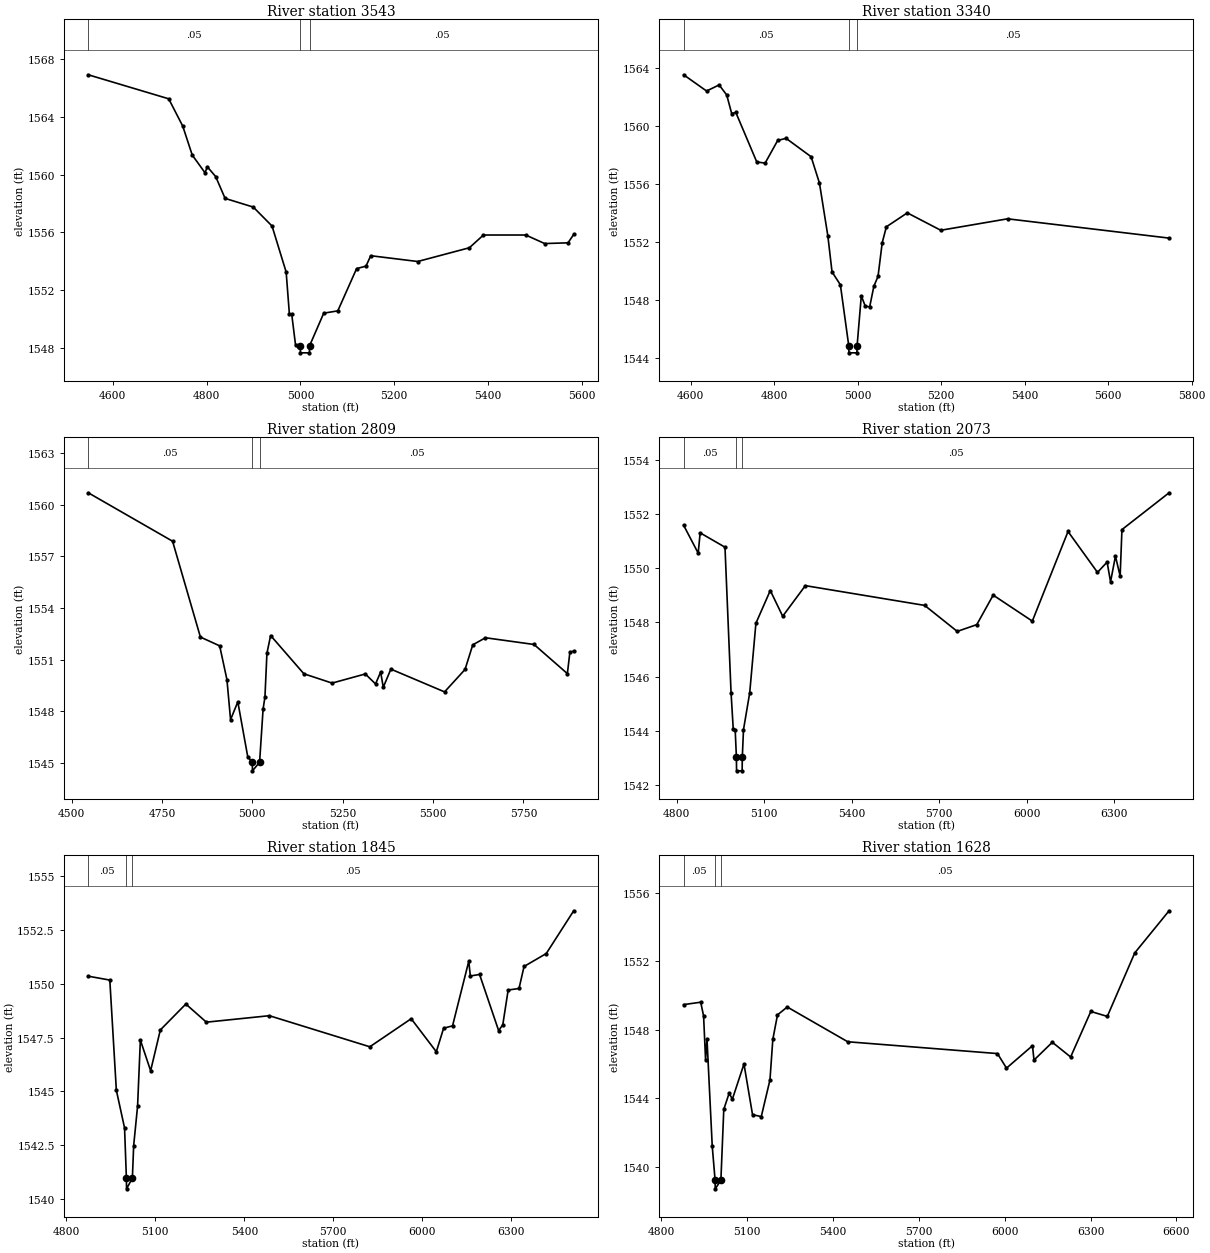
Type RM Length L Ch R = 1,3543,203,203,203
BEGIN DESCRIPTION:
Mapping XS f5b30deb
END DESCRIPTION:
XS GIS Cut Line= 2
      1625164.01      6941386.78      1625106.29      6942420.07
#Sta/Elev= 30
  4547.6 1566.89  4719.1 1565.23  4749.1 1563.34  4769.2 1561.35  4796.5 1560.12
  4801.5 1560.53  4819.2 1559.86  4839.3 1558.35  4899.4 1557.75  4939.4 1556.44
  4969.5 1553.26  4976.3 1550.39  4981.3 1550.36  4989.5 1548.22  4999.5 1548.18
  5000.0 1547.68  5019.1 1547.68  5019.6 1548.18  5049.6 1550.42  5079.6 1550.58
  5119.7 1553.50  5139.7 1553.67  5149.8 1554.39  5249.9 1553.99  5360.1 1554.94
  5390.1 1555.82  5480.3 1555.82  5520.6 1555.23  5570.4 1555.28  5582.5 1555.86
#Mann=3,-1,0
  4547.6    0.05       0  4999.5    0.03       0  5019.6    0.05       0
Bank Sta=4999.5,5019.6
Exp/Cntr=0.3,0.1

Type RM Length L Ch R = 1,3340,531,531,531
BEGIN DESCRIPTION:
Mapping XS 3a145b9e
END DESCRIPTION:
XS GIS Cut Line= 3
      1624986.38      6941413.14      1624949.01      6942034.83
      1624933.12      6942574.69
#Sta/Elev= 30
  4583.0 1563.56  4638.0 1562.44  4668.0 1562.86  4686.2 1562.17  4698.1 1560.89
  4708.1 1560.96  4758.2 1557.55  4778.2 1557.47  4808.3 1559.03  4828.3 1559.18
  4888.4 1557.91  4908.4 1556.09  4928.5 1552.45  4938.5 1549.97  4958.5 1549.08
  4978.5 1544.89  4979.0 1544.39  4998.1 1544.39  4998.6 1544.89  5008.6 1548.32
  5018.1 1547.61  5028.7 1547.56  5038.7 1548.98  5048.7 1549.66  5058.7 1551.98
  5068.7 1553.08  5118.8 1554.04  5199.0 1552.84  5359.0 1553.63  5745.9 1552.30
#Mann=3,-1,0
  4583.0    0.05       0  4978.5    0.03       0  4998.6    0.05       0
Bank Sta=4978.5,4998.6
Exp/Cntr=0.3,0.1

Type RM Length L Ch R = 1,2809,736,736,736
BEGIN DESCRIPTION:
Mapping XS 4d4d463a
END DESCRIPTION:
XS GIS Cut Line= 4
      1624533.74      6941535.52      1624497.53      6942010.22
      1624537.24      6942201.38      1625000.39      6942687.43
#Sta/Elev= 30
  4546.3 1560.68  4779.5 1557.87  4856.5 1552.31  4909.8 1551.80  4929.9 1549.84
  4939.9 1547.52  4960.0 1548.55  4987.5 1545.36  5000.0 1545.05  5000.5 1544.55
  5020.2 1545.05  5029.9 1548.14  5035.0 1548.83  5040.5 1551.37  5050.7 1552.40
  5142.7 1550.18  5220.7 1549.64  5312.6 1550.17  5340.9 1549.59  5355.0 1550.28
  5362.3 1549.40  5383.3 1550.45  5531.8 1549.13  5588.4 1550.43  5609.8 1551.86
  5645.0 1552.27  5779.3 1551.88  5871.5 1550.19  5878.4 1551.43  5889.0 1551.50
#Mann=3,-1,0
  4546.3    0.05       0  5000.0    0.05       0  5020.2    0.05       0
Bank Sta=5000,5020.2
Exp/Cntr=0.3,0.1

Type RM Length L Ch R = 1,2073,228,228,228
BEGIN DESCRIPTION:
Mapping XS 24ba0cf8
END DESCRIPTION:
XS GIS Cut Line= 3
      1623717.06      6941925.73      1624063.05      6942239.53
      1625135.19      6942774.96
#Sta/Elev= 30
  4823.2 1551.59  4873.2 1550.56  4879.9 1551.31  4965.1 1550.78  4986.0 1545.39
  4993.5 1544.05  5000.2 1544.01  5004.3 1543.02  5004.8 1542.52  5024.0 1542.52
  5024.5 1543.02  5028.6 1544.04  5049.9 1545.40  5071.2 1547.97  5120.5 1549.18
  5163.1 1548.23  5240.8 1549.36  5650.2 1548.63  5761.9 1547.67  5829.0 1547.92
  5885.2 1549.01  6019.5 1548.05  6142.0 1551.36  6243.1 1549.85  6276.1 1550.23
  6287.9 1549.50  6304.7 1550.45  6320.8 1549.71  6327.0 1551.43  6488.7 1552.79
#Mann=3,-1,0
  4823.2    0.05       0  5004.3    0.05       0  5024.5    0.05       0
Bank Sta=5004.3,5024.5
Exp/Cntr=0.3,0.1

Type RM Length L Ch R = 1,1845,217,217,217
BEGIN DESCRIPTION:
Mapping XS 4175ff58
END DESCRIPTION:
XS GIS Cut Line= 3
      1623639.73      6942176.83      1623930.77      6942331.12
      1625151.33      6942799.36
#Sta/Elev= 30
  4873.8 1550.34  4946.5 1550.16  4968.5 1545.06  4996.2 1543.31  5002.4 1540.99
  5002.9 1540.49  5022.6 1540.99  5026.9 1542.49  5040.1 1544.32  5049.5 1547.38
  5084.1 1545.96  5116.8 1547.85  5202.8 1549.05  5272.0 1548.21  5484.3 1548.51
  5823.1 1547.07  5962.6 1548.37  6047.3 1546.84  6071.9 1547.93  6102.0 1548.04
  6156.7 1551.03  6162.0 1550.35  6193.1 1550.42  6257.4 1547.82  6271.4 1548.09
  6289.5 1549.70  6326.1 1549.77  6343.1 1550.79  6418.0 1551.39  6510.5 1553.37
#Mann=3,-1,0
  4873.8    0.05       0  5002.4    0.05       0  5022.6    0.05       0
Bank Sta=5002.4,5022.6
Exp/Cntr=0.3,0.1

Type RM Length L Ch R = 1,1628,309,309,309
BEGIN DESCRIPTION:
Mapping XS 971dfa2e
END DESCRIPTION:
XS GIS Cut Line= 3
      1623585.82      6942423.59      1623988.63      6942472.21
      1625214.91      6942869.59
#Sta/Elev= 30
  4879.4 1549.48  4939.0 1549.62  4949.1 1548.82  4956.0 1546.26  4961.0 1547.48
  4979.3 1541.21  4989.3 1539.22  4989.8 1538.72  5009.5 1539.22  5019.6 1543.36
  5038.0 1544.29  5049.8 1543.97  5090.1 1546.01  5120.0 1543.05  5150.5 1542.94
  5180.8 1545.08  5190.8 1547.45  5207.1 1548.88  5241.2 1549.34  5452.3 1547.31
  5975.1 1546.62  6006.6 1545.77  6097.3 1547.08  6102.6 1546.24  6166.6 1547.28
  6230.5 1546.42  6301.0 1549.08  6358.5 1548.79  6454.4 1552.50  6574.2 1554.96
#Mann=3,-1,0
  4879.4    0.05       0  4989.3    0.05       0  5009.5    0.05       0
Bank Sta=4989.3,5009.5
Exp/Cntr=0.3,0.1

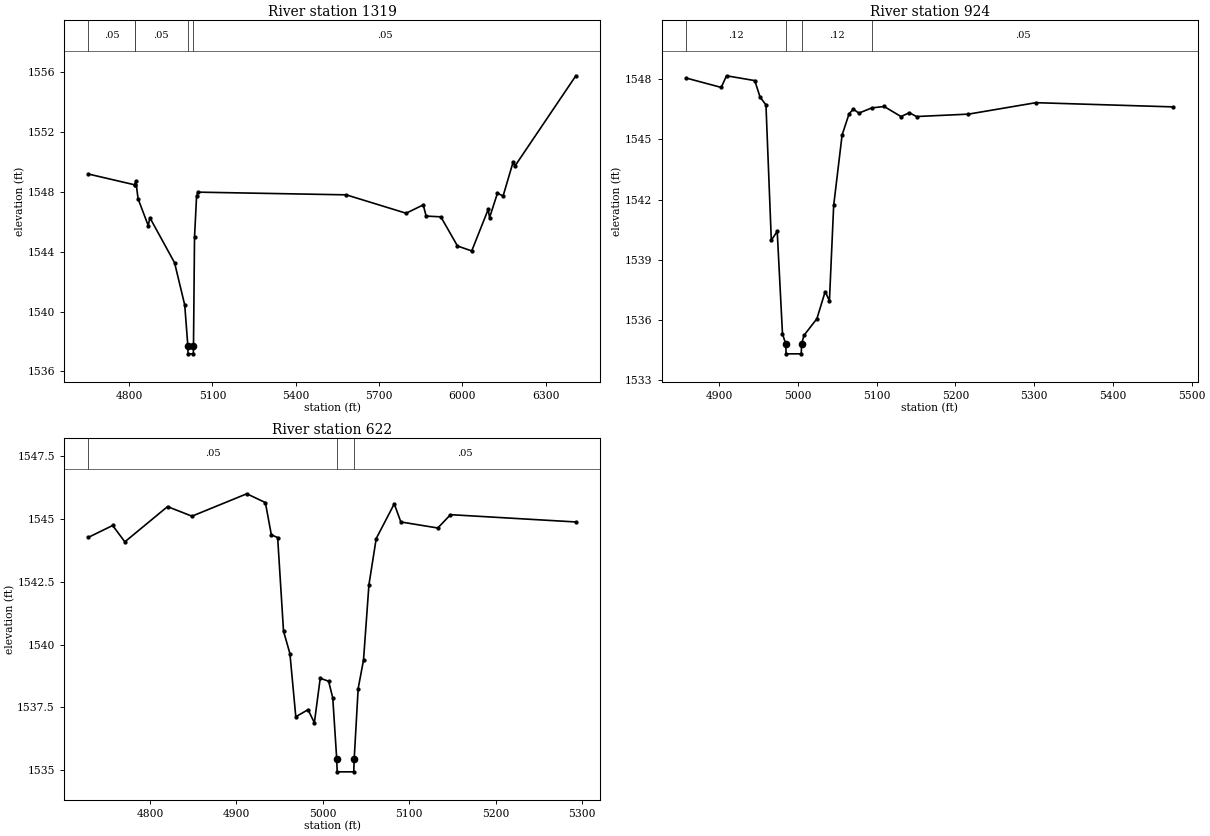
Type RM Length L Ch R = 1,1319,395,395,395
BEGIN DESCRIPTION:
Mapping XS b2a076b5
END DESCRIPTION:
XS GIS Cut Line= 3
      1623559.82      6942508.39      1623897.80      6942716.16
      1625219.90      6943023.97
#Sta/Elev= 30
  4653.8 1549.20  4820.2 1548.48  4820.4 1548.49  4824.2 1548.74  4832.3 1547.55
  4869.0 1545.75  4874.8 1546.28  4963.7 1543.27  5000.3 1540.44  5011.6 1537.68
  5012.1 1537.18  5031.3 1537.18  5031.8 1537.68  5035.5 1544.97  5042.9 1547.71
  5047.5 1547.99  5581.6 1547.81  5797.2 1546.58  5858.8 1547.14  5869.1 1546.39
  5922.1 1546.34  5982.0 1544.39  6033.3 1544.06  6092.4 1546.83  6097.5 1546.29
  6125.7 1547.91  6146.3 1547.74  6182.7 1550.03  6187.9 1549.71  6408.0 1555.77
#Mann=5,-1,0
  4653.8    0.05       0  4820.2    0.12       0  4820.4    0.05       0
  5011.6    0.03       0  5031.8    0.05       0
Bank Sta=5011.6,5031.8
Exp/Cntr=0.3,0.1

Type RM Length L Ch R = 1,924,302,302,302
BEGIN DESCRIPTION:
Mapping XS 83d40698
END DESCRIPTION:
XS GIS Cut Line= 3
      1623559.82      6942839.95      1623659.69      6942951.80
      1624099.11      6943115.59
#Sta/Elev= 30
  4857.8 1548.06  4902.6 1547.59  4909.3 1548.17  4945.2 1547.93  4951.9 1547.11
  4959.4 1546.72  4966.2 1539.98  4973.7 1540.42  4980.4 1535.31  4984.5 1534.82
  4985.0 1534.32  5004.2 1534.32  5004.7 1534.82  5007.7 1535.24  5024.1 1536.07
  5034.6 1537.42  5040.0 1536.96  5045.4 1541.71  5056.1 1545.22  5064.9 1546.27
  5070.3 1546.51  5077.4 1546.31  5093.8 1546.57  5109.5 1546.64  5130.9 1546.14
  5141.5 1546.33  5150.6 1546.14  5216.6 1546.26  5302.2 1546.83  5476.7 1546.62
#Mann=4,-1,0
  4857.8    0.12       0  4984.5    0.07       0  5004.7    0.12       0
  5093.8    0.05       0
Bank Sta=4984.5,5004.7
Exp/Cntr=0.3,0.1

Type RM Length L Ch R = 1,622,0,0,0
BEGIN DESCRIPTION:
Threemile Creek 1.0
END DESCRIPTION:
XS GIS Cut Line= 3
      1623428.01      6943035.72      1623617.10      6943239.57
      1623849.72      6943406.22
#Sta/Elev= 30
  4728.8 1544.26  4756.8 1544.73  4770.9 1544.08  4820.3 1545.48  4848.6 1545.10
  4912.1 1545.99  4933.6 1545.64  4940.5 1544.36  4947.8 1544.25  4954.6 1540.53
  4962.0 1539.64  4968.8 1537.13  4983.0 1537.41  4990.3 1536.89  4997.1 1538.66
  5006.8 1538.54  5011.6 1537.88  5016.2 1535.44  5016.7 1534.94  5035.9 1534.94
  5036.4 1535.44  5041.0 1538.25  5047.2 1539.38  5053.5 1542.38  5061.9 1544.21
  5082.8 1545.59  5090.4 1544.87  5133.2 1544.63  5147.9 1545.16  5293.0 1544.87
#Mann=3,-1,0
  4728.8    0.05       0  5016.2    0.03       0  5036.4    0.05       0
Bank Sta=5016.2,5036.4
Exp/Cntr=0.3,0.1

Chan Stop Cuts=-1