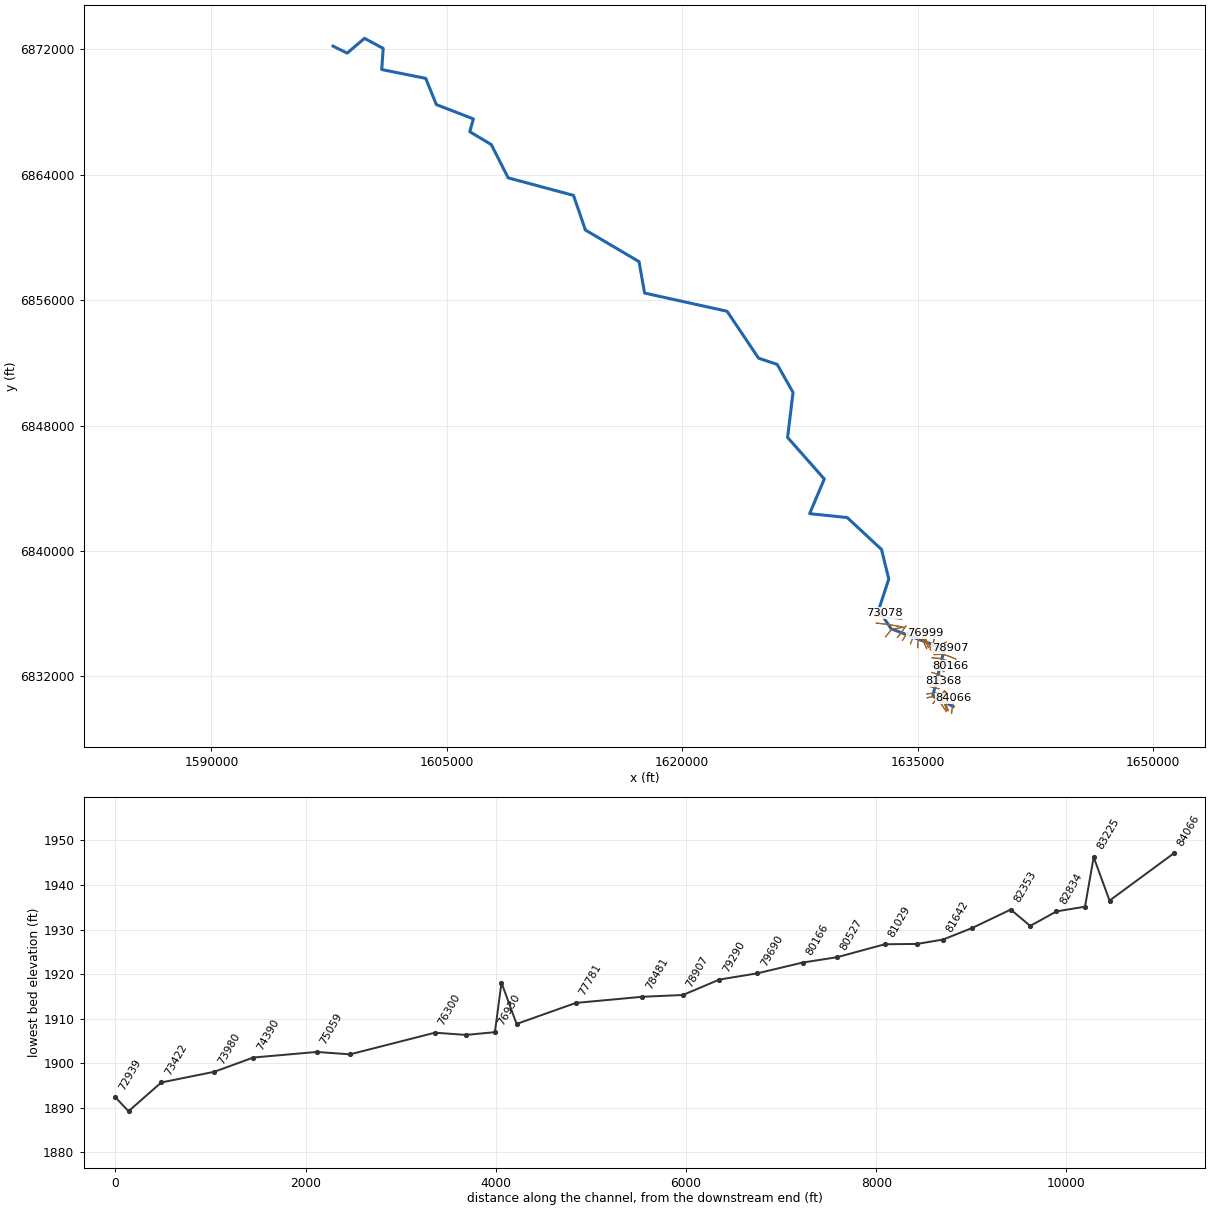
--- Buck Creek.prj (project) ---

Proj Title=Buck Creek Base Level Engineering
Current Plan=p01
Default Exp/Contr=0.3,0.1
English Units
Geom File=g01
Flow File=f01
Plan File=p01
Y Axis Title=Elevation
X Axis Title(PF)=Main Channel Distance
X Axis Title(XS)=Station
BEGIN DESCRIPTION:
Buck Creek
END DESCRIPTION:
DSS Export Rating Curves= 0
DSS Export Rating Curve Sorted= 0
DSS Export Volume Flow Curves= 0
DXF OffsetX= 0
DXF OffsetY= 0
DXF ScaleX= 1
DXF ScaleY= 10

--- Buck Creek.p01 (plan) ---

Plan Title=Multiple Run
Short Identifier=Multiple
Geom File=g01
Flow File=f01
Subcritical Flow
K Sum by GR= 0
Std Step Tol= 0.01
Critical Tol= 0.01
Num of Std Step Trials= 20
Max Error Tol= 0.3
Flow Tol Ratio= 0.001
Split Flow NTrial= 30
Split Flow Tol= 0.02
Split Flow Ratio= 0.02
Log Output Level= 0
Friction Slope Method= 1
Unsteady Friction Slope Method= 2
Unsteady Bridges Friction Slope Method= 1
Parabolic Critical Depth
Global Vel Dist=  1 , 1 , 1
Global Log Level= 0
CheckData=True
Encroach Param= -1, 0, 0, 0
BEGIN DESCRIPTION:
Multiple Run
END DESCRIPTION:

--- Buck Creek.f01 (steady flow) ---

Flow Title=Multiple
Program Version=4.10
Number of Profiles= 7
Profile Names=10-year,25-year,50-year,1pct_min,100-year,1pct_plu,500-year
River Rch & RM=Buck Creek,Reach-1         ,84066
     207     282     343     259     415     571     614
River Rch & RM=Buck Creek,Reach-1         ,83225
     386     546     681     526     844    1160    1310
River Rch & RM=Buck Creek,Reach-1         ,80166
     504     723     909     708    1130    1560    1790
River Rch & RM=Buck Creek,Reach-1         ,77781
     578     835    1060     826    1320    1820    2110
River Rch & RM=Buck Creek,Reach-1         ,69443
     658     958    1220     955    1530    2110    2460
River Rch & RM=Buck Creek,Reach-1         ,67306
     734    1070    1360    1070    1720    2360    2770
River Rch & RM=Buck Creek,Reach-1         ,59042
     804    1180    1500    1180    1900    2610    3070
River Rch & RM=Buck Creek,Reach-1         ,52428
     974    1430    1830    1450    2320    3200    3780
River Rch & RM=Buck Creek,Reach-1         ,46902
    1010    1480    1900    1500    2400    3310    3910
River Rch & RM=Buck Creek,Reach-1         ,44121
    1070    1580    2020    1600    2560    3530    4170
River Rch & RM=Buck Creek,Reach-1         ,40381
    1110    1640    2100    1660    2670    3670    4340
River Rch & RM=Buck Creek,Reach-1         ,31598
    1200    1770    2270    1800    2880    3960    4700
River Rch & RM=Buck Creek,Reach-1         ,22676
    1420    2120    2730    2170    3470    4780    5710
River Rch & RM=Buck Creek,Reach-1         ,21745
    1420    2120    2730    2170    3470    4780    5710
River Rch & RM=Buck Creek,Reach-1         ,19284
    1430    2130    2740    2180    3490    4800    5720
River Rch & RM=Buck Creek,Reach-1         ,18817
    1570    2340    3020    2400    3850    5290    6330
River Rch & RM=Buck Creek,Reach-1         ,15117
    1570    2340    3020    2400    3850    5290    6330
River Rch & RM=Buck Creek,Reach-1         ,12704
    1590    2370    3050    2430    3890    5350    6400
River Rch & RM=Buck Creek,Reach-1         ,12046
    1600    2380    3080    2450    3920    5390    6450
River Rch & RM=Buck Creek,Reach-1         ,10870
    1620    2410    3110    2470    3960    5450    6520
River Rch & RM=Buck Creek,Reach-1         ,3765
    1640    2450    3160    2510    4020    5530    6610
Boundary for River Rch & Prof#=Buck Creek,Reach-1         , 1
Up Type= 0
Dn Type= 3
Dn Slope=0.001
Boundary for River Rch & Prof#=Buck Creek,Reach-1         , 2
Up Type= 0
Dn Type= 3
Dn Slope=0.001
Boundary for River Rch & Prof#=Buck Creek,Reach-1         , 3
Up Type= 0
Dn Type= 3
Dn Slope=0.001
Boundary for River Rch & Prof#=Buck Creek,Reach-1         , 4
Up Type= 0
Dn Type= 3
Dn Slope=0.001
Boundary for River Rch & Prof#=Buck Creek,Reach-1         , 5
Up Type= 0
Dn Type= 3
Dn Slope=0.001
Boundary for River Rch & Prof#=Buck Creek,Reach-1         , 6
Up Type= 0
Dn Type= 3
Dn Slope=0.001
Boundary for River Rch & Prof#=Buck Creek,Reach-1         , 7
Up Type= 0
Dn Type= 3
Dn Slope=0.001
DSS Import GetInterval= 0
DSS Import GetPeak= 0
DSS Import FillOption= 0

--- Buck Creek.g01 (geometry) ---

Geom Title=Existing Conditions
Program Version=4.10

River Reach=Buck Creek      ,Reach-1
Reach XY= 30
        1637255.        6830088.      1635955.53      6830751.86
      1636694.24      6833747.68       1633302.7      6835043.83
      1632508.54      6836239.46      1633155.24      6838212.92
      1632694.23       6840097.7        1630507.      6842133.02
      1628114.11      6842381.27       1629047.4      6844591.32
      1626708.54      6847239.46      1627055.43      6850110.95
      1626044.52      6851897.85      1624860.19      6852293.44
      1622853.54      6855284.46      1617598.79       6856445.8
      1617244.25      6858447.71      1613827.86      6860464.47
      1613071.68      6862671.36      1608906.63      6863791.15
      1607832.14      6865911.53      1606462.47      6866731.92
      1606694.59      6867547.77      1604331.48      6868460.98
      1603657.32      6870132.21      1600852.71      6870693.84
      1600947.26      6872044.59       1599753.5      6872684.53
      1598649.38      6871739.98        1597755.        6872188.

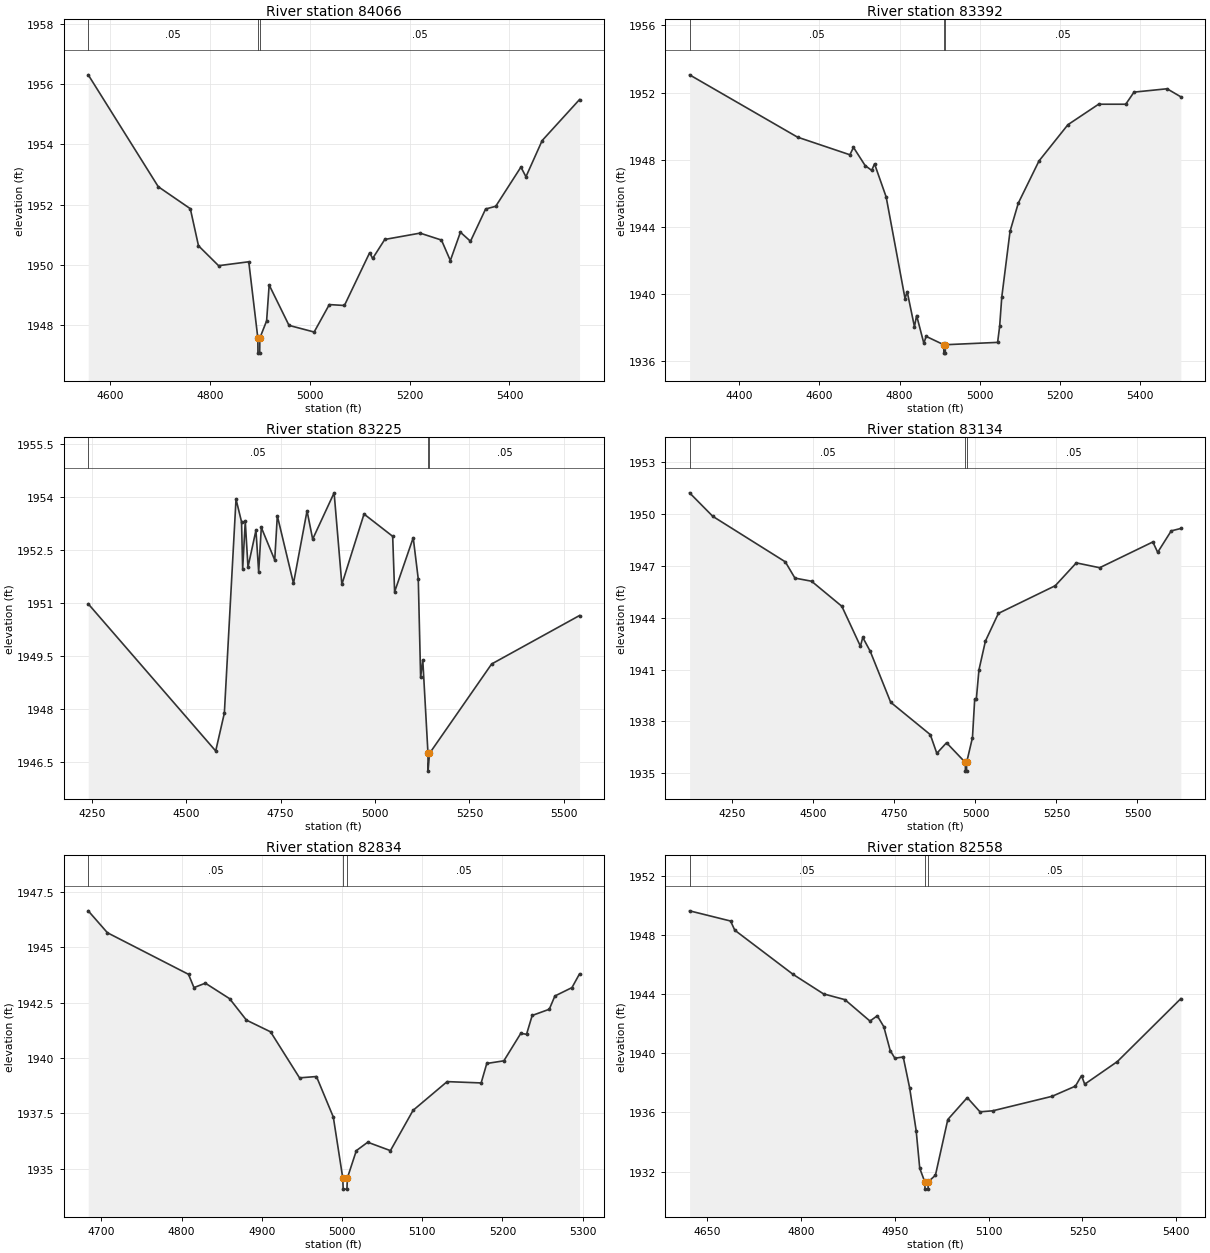
Type RM Length L Ch R = 1 ,84066   ,674,674,674
BEGIN DESCRIPTION:
Buck Creek 83868.144
END DESCRIPTION:
XS GIS Cut Line= 3
      1637153.73       6829648.8      1637211.14      6830089.68
      1637291.57      6830624.16
#Sta/Elev= 30
  4555.4 1956.31  4695.8  1952.6  4760.1 1951.87  4776.5 1950.64  4816.8 1949.98
  4877.3 1950.11  4895.5 1947.58  4895.7 1947.08  4899.2 1947.08  4899.5 1947.58
  4913.1 1948.15  4918.2 1949.34    4958    1948  5008.4 1947.78  5038.8 1948.69
  5069.1 1948.66  5119.7 1950.41  5125.7 1950.22    5150 1950.85  5220.8 1951.06
  5263.7 1950.83  5281.5 1950.15  5301.7 1951.09  5321.9 1950.79  5352.2 1951.86
  5372.5 1951.95    5423 1953.25  5433.1 1952.93  5465.6 1954.13  5540.5 1955.49
#Mann= 3 ,-1 , 0
  4555.4     .05       0  4895.5     .05       0  4899.5     .05       0
Bank Sta=4895.5,4899.5
XS Rating Curve= 0 ,0
Exp/Cntr=0.3,0.1

Type RM Length L Ch R = 1 ,83392   ,167,167,167
BEGIN DESCRIPTION:
Buck Creek 83391.98
END DESCRIPTION:
XS GIS Cut Line= 4
       1636953.2      6829820.64      1636718.83       6830364.9
        1636698.      6830495.11      1636820.21      6830981.35
#Sta/Elev= 30
    4276 1953.06  4545.3 1949.35    4676  1948.3    4685 1948.74    4714 1947.66
  4730.4 1947.37  4737.5 1947.76  4766.5 1945.79  4813.6 1939.74    4819 1940.15
  4837.1 1938.06  4842.5 1938.73  4860.6 1937.07  4866.1 1937.49  4910.2 1936.99
  4910.5 1936.49    4914 1936.49  4914.2 1936.99  5044.6 1937.13  5049.7 1938.09
    5055 1939.83  5075.6 1943.74  5096.2 1945.42  5147.8 1947.93    5220 1950.09
  5296.6 1951.31  5364.3 1951.31  5384.9 1952.03  5467.4 1952.23  5501.8 1951.75
#Mann= 3 ,-1 , 0
    4276     .05       0  4910.2     .05       0  4914.2     .05       0
Bank Sta=4910.2,4914.2
XS Rating Curve= 0 ,0
Exp/Cntr=0.3,0.1

Type RM Length L Ch R = 1 ,83225   ,91,91,91
BEGIN DESCRIPTION:
Buck Creek 83225.24
END DESCRIPTION:
XS GIS Cut Line= 6
      1636849.03      6829859.73      1636713.62       6830242.5
      1636630.29      6830328.44      1636549.56      6830445.63
      1636554.77      6830651.36      1636768.31      6831021.16
#Sta/Elev= 30
  4240.5 1950.98  4578.1 1946.82    4601 1947.89  4631.9 1953.94  4646.5  1953.3
  4649.5 1951.97  4656.4 1953.31  4663.6 1952.02  4684.7 1953.06  4691.9 1951.88
  4698.9 1953.14  4734.4 1952.22  4741.3 1953.47  4784.1 1951.56    4820 1953.61
  4834.9 1952.81  4891.7 1954.12  4912.2 1951.53  4970.9 1953.52  5046.8 1952.89
  5051.9 1951.32  5101.2 1952.85  5114.6 1951.68  5120.8  1948.9  5126.5  1949.4
  5140.3 1946.75  5140.5 1946.25  5144.3 1946.75  5308.9 1949.28  5541.6 1950.65
#Mann= 3 ,-1 , 0
  4240.5     .05       0  5140.3     .05       0  5144.3     .05       0
Bank Sta=5140.3,5144.3
XS Rating Curve= 0 ,0
Exp/Cntr=0.3,0.1

Type RM Length L Ch R = 1 ,83134   ,300,300,300
BEGIN DESCRIPTION:
Buck Creek 83133.97
END DESCRIPTION:
XS GIS Cut Line= 5
       1636817.8      6829760.72      1636463.62       6830302.4
      1636455.81      6830536.77      1636461.02      6830734.69
      1636710.13      6831092.79
#Sta/Elev= 30
  4117.9 1951.22  4189.6 1949.86  4413.3 1947.23    4443 1946.29  4494.3 1946.11
  4587.8 1944.66  4645.1 1942.35  4652.3 1942.86  4675.3 1942.06  4738.5 1939.11
  4860.7 1937.24  4880.8 1936.16  4910.8 1936.77  4968.8 1935.63  4969.1 1935.13
  4972.6 1935.13  4972.8 1935.63  4990.8 1937.07  4997.7 1939.29  5002.7 1939.29
  5010.8 1940.98  5030.8 1942.65  5070.8 1944.25  5246.3 1945.85  5311.2 1947.17
  5383.3 1946.89  5547.4 1948.38  5562.3 1947.78  5604.1 1949.02  5633.8 1949.16
#Mann= 3 ,-1 , 0
  4117.9     .05       0  4968.8     .05       0  4972.8     .05       0
Bank Sta=4968.8,4972.8
XS Rating Curve= 0 ,0
Exp/Cntr=0.3,0.1

Type RM Length L Ch R = 1 ,82834   ,276,276,276
BEGIN DESCRIPTION:
Buck Creek 82833.74
END DESCRIPTION:
XS GIS Cut Line= 3
       1635981.5      6830278.09      1636159.46      6830547.19
      1636362.19      6830754.24
#Sta/Elev= 30
  4683.7 1946.65  4707.6 1945.66  4808.7 1943.78  4815.5 1943.18  4829.7 1943.38
  4859.9 1942.68  4880.9 1941.71    4911 1941.18  4947.1  1939.1  4968.2 1939.16
  4989.2 1937.33    5001 1934.57  5001.5 1934.07  5006.2 1934.07  5006.7 1934.57
  5017.9 1935.81  5032.1 1936.19  5060.4 1935.81  5088.6 1937.63  5131.1 1938.93
  5173.5 1938.87  5180.5 1939.75  5201.8 1939.87  5222.9 1941.11  5230.1 1941.07
  5237.1 1941.92  5258.4  1942.2  5265.4  1942.8  5286.7 1943.18  5296.1  1943.8
#Mann= 3 ,-1 , 0
  4683.7     .05       0    5001     .05       0  5006.7     .05       0
Bank Sta=5001,5006.7
XS Rating Curve= 0 ,0
Exp/Cntr=0.3,0.1

Type RM Length L Ch R = 1 ,82558   ,205,205,205
BEGIN DESCRIPTION:
Buck Creek 82558.16
END DESCRIPTION:
XS GIS Cut Line= 3
      1635595.24      6830636.17      1635961.97      6830735.99
      1636360.65      6830811.83
#Sta/Elev= 30
  4621.5 1949.64  4687.1 1948.95  4693.8 1948.33  4787.1 1945.34  4835.8 1944.02
    4870 1943.63  4910.1 1942.18  4921.8 1942.54  4932.2  1941.8  4942.5 1940.18
  4949.9 1939.67  4963.3 1939.75  4973.6 1937.65    4984 1934.76  4989.7 1932.22
  4997.7 1931.31  4998.2 1930.81    5003 1930.81  5003.4 1931.31  5014.8 1931.75
  5034.6 1935.52  5065.7    1937  5086.1 1936.04  5106.5 1936.11  5201.4 1937.09
  5238.8 1937.78  5248.5 1938.49  5253.6 1937.91  5305.8 1939.44  5407.4  1943.7
#Mann= 3 ,-1 , 0
  4621.5     .05       0  4997.7     .05       0  5003.4     .05       0
Bank Sta=4997.7,5003.4
XS Rating Curve= 0 ,0
Exp/Cntr=0.3,0.1

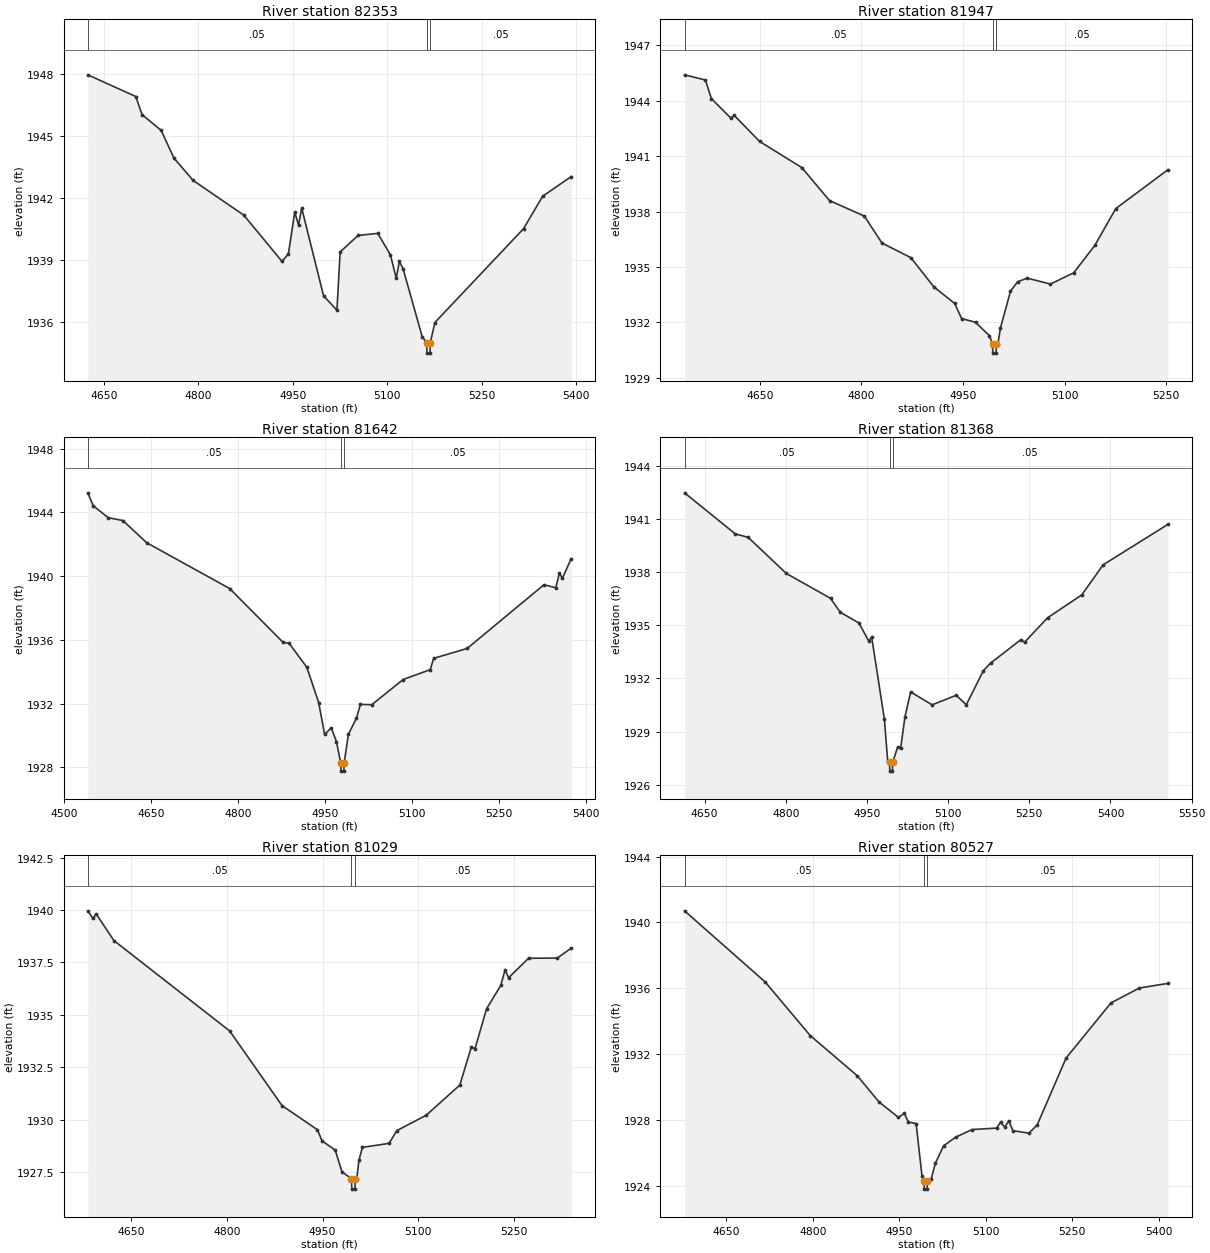
Type RM Length L Ch R = 1 ,82353   ,406,406,406
BEGIN DESCRIPTION:
Buck Creek 82353.33
END DESCRIPTION:
XS GIS Cut Line= 4
      1635589.65      6830885.21      1635960.76       6830938.6
      1636018.05      6830950.32        1636350.      6830909.96
#Sta/Elev= 30
  4624.6 1947.96  4700.7 1946.91  4710.8 1946.03  4741.1 1945.27  4761.3 1943.93
  4791.7 1942.85  4872.5 1941.16  4933.1 1938.92  4943.2 1939.29  4953.3 1941.31
  4959.3 1940.68  4964.3 1941.51  4999.1 1937.25  5020.3 1936.56  5025.4 1939.38
  5053.9 1940.18  5085.2 1940.28  5105.3 1939.24  5114.5  1938.1  5119.5 1938.93
  5125.5 1938.55  5155.7 1935.28  5162.9 1934.98  5163.3 1934.48  5168.1 1934.48
  5168.6 1934.98  5175.8 1935.96  5316.8 1940.51  5347.1 1942.08  5392.4 1943.03
#Mann= 3 ,-1 , 0
  4624.6     .05       0  5162.9     .05       0  5168.6     .05       0
Bank Sta=5162.9,5168.6
XS Rating Curve= 0 ,0
Exp/Cntr=0.3,0.1

Type RM Length L Ch R = 1 ,81947   ,305,305,305
BEGIN DESCRIPTION:
Buck Creek 81947.24
END DESCRIPTION:
XS GIS Cut Line= 3
      1635656.44      6831389.16      1636104.33        6831285.
       1636349.1       6831217.3
#Sta/Elev= 30
  4538.7 1945.41  4569.5 1945.13  4578.3 1944.12    4607 1943.07  4612.1 1943.21
  4649.6  1941.8  4711.8 1940.39  4752.8  1938.6  4804.2 1937.76  4830.3  1936.3
  4872.9 1935.51  4906.8 1933.93  4937.6 1933.03  4947.9 1932.21  4968.4 1932.01
    4989 1931.28  4993.5 1930.84  4993.9 1930.34  4998.7 1930.34  4999.2 1930.84
  5001.5 1930.84  5005.2  1931.7    5020 1933.69  5030.4  1934.2  5044.7  1934.4
  5079.1 1934.08  5113.4 1934.69  5144.5 1936.17  5175.6 1938.17  5252.5 1940.27
#Mann= 3 ,-1 , 0
  4538.7     .05       0  4993.5     .05       0  4999.2     .05       0
Bank Sta=4993.5,4999.2
XS Rating Curve= 0 ,0
Exp/Cntr=0.3,0.1

Type RM Length L Ch R = 1 ,81642   ,274,274,274
BEGIN DESCRIPTION:
Buck Creek 81642.34
END DESCRIPTION:
XS GIS Cut Line= 3
      1635705.86      6831670.43      1636153.81      6831574.06
      1636510.28      6831456.98
#Sta/Elev= 30
  4541.6 1945.23  4550.9 1944.42  4576.7 1943.67  4602.1 1943.49    4643  1942.1
  4786.2 1939.22  4878.3 1935.84  4888.5 1935.79  4919.2 1934.28  4939.6 1932.06
  4949.9 1930.06  4961.3 1930.48  4970.3 1929.61  4977.7 1928.26  4978.2 1927.76
    4983 1927.76  4983.5 1928.26  4990.8 1930.06  5004.8 1931.09  5011.6 1931.95
  5031.3 1931.93  5085.2 1933.51    5132 1934.13  5137.9 1934.84  5195.6 1935.46
  5328.1 1939.46  5348.4 1939.27  5354.7 1940.18  5359.9 1939.87    5375  1941.1
#Mann= 3 ,-1 , 0
  4541.6     .05       0  4977.7     .03       0  4983.5     .05       0
Bank Sta=4977.7,4983.5
XS Rating Curve= 0 ,0
Exp/Cntr=0.3,0.1

Type RM Length L Ch R = 1 ,81368   ,339,339,339
BEGIN DESCRIPTION:
Buck Creek 81367.58
END DESCRIPTION:
XS GIS Cut Line= 3
      1635810.09      6831998.53      1636161.63       6831847.5
      1636646.01      6831686.04
#Sta/Elev= 30
  4612.9 1942.47  4706.8 1940.15  4730.4 1939.96    4801 1937.92  4882.6 1936.52
  4900.7 1935.73  4935.1 1935.13  4953.2 1934.11  4958.7 1934.33  4982.2 1929.69
  4988.3 1927.34  4991.7 1927.27  4992.2 1926.77    4997 1926.77  4997.5 1927.27
    5007 1928.15  5012.3 1928.07  5020.2 1929.83  5030.7 1931.24  5070.3 1930.51
    5115 1931.05  5133.5 1930.51  5165.2 1932.44  5178.3 1932.86  5233.7 1934.17
  5241.5 1934.05  5283.7 1935.42  5346.9 1936.71  5386.5 1938.41  5506.1 1940.69
#Mann= 3 ,-1 , 0
  4612.9     .05       0  4991.7     .03       0  4997.5     .05       0
Bank Sta=4991.7,4997.5
XS Rating Curve= 0 ,0
Exp/Cntr=0.3,0.1

Type RM Length L Ch R = 1 ,81029   ,502,502,502
BEGIN DESCRIPTION:
Buck Creek 81028.78
END DESCRIPTION:
XS GIS Cut Line= 3
      1635903.19      6832255.48       1636304.2       6832135.7
      1636616.54      6832002.95
#Sta/Elev= 30
    4582 1939.96  4589.9  1939.6  4595.1 1939.81    4623 1938.54  4804.3 1934.24
  4886.5 1930.68    4942 1929.53  4949.2    1929  4969.9 1928.56  4980.5 1927.52
  4995.4  1927.2  4995.9  1926.7  5000.8  1926.7  5001.2  1927.2  5003.7  1927.2
  5007.1 1928.07  5012.5 1928.69  5054.4 1928.88  5066.6 1929.49  5112.6 1930.22
  5165.3 1931.66  5183.5 1933.49    5189 1933.38  5207.2 1935.29  5229.6 1936.41
  5236.3 1937.16  5241.7 1936.77    5273  1937.7  5318.1 1937.71  5339.9 1938.18
#Mann= 3 ,-1 , 0
    4582     .05       0  4995.4     .05       0  5001.2     .05       0
Bank Sta=4995.4,5001.2
XS Rating Curve= 0 ,0
Exp/Cntr=0.3,0.1

Type RM Length L Ch R = 1 ,80527   ,361,361,361
BEGIN DESCRIPTION:
Buck Creek 80526.51
END DESCRIPTION:
XS GIS Cut Line= 3
      1635941.34      6832670.42      1636352.82      6832587.09
       1636665.3      6832308.45
#Sta/Elev= 30
  4577.7  1940.7  4717.5 1936.38  4795.7 1933.12  4877.3 1930.68  4915.2 1929.08
  4948.7 1928.15  4958.9 1928.39  4965.9 1927.87  4979.4 1927.77  4989.6 1924.59
  4993.1 1924.29  4993.6 1923.79  4998.5 1923.79    4999 1924.29  5005.4 1924.38
  5012.9 1925.37  5027.1 1926.42  5048.1 1926.95  5076.5 1927.41  5119.1  1927.5
  5125.8 1927.85  5133.3 1927.56    5140 1927.94  5147.5 1927.34  5175.1 1927.19
  5189.4 1927.69  5239.5 1931.75  5317.3  1935.1  5366.6 1936.01  5416.2 1936.29
#Mann= 3 ,-1 , 0
  4577.7     .05       0  4993.1     .05       0    4999     .05       0
Bank Sta=4993.1,4999
XS Rating Curve= 0 ,0
Exp/Cntr=0.3,0.1

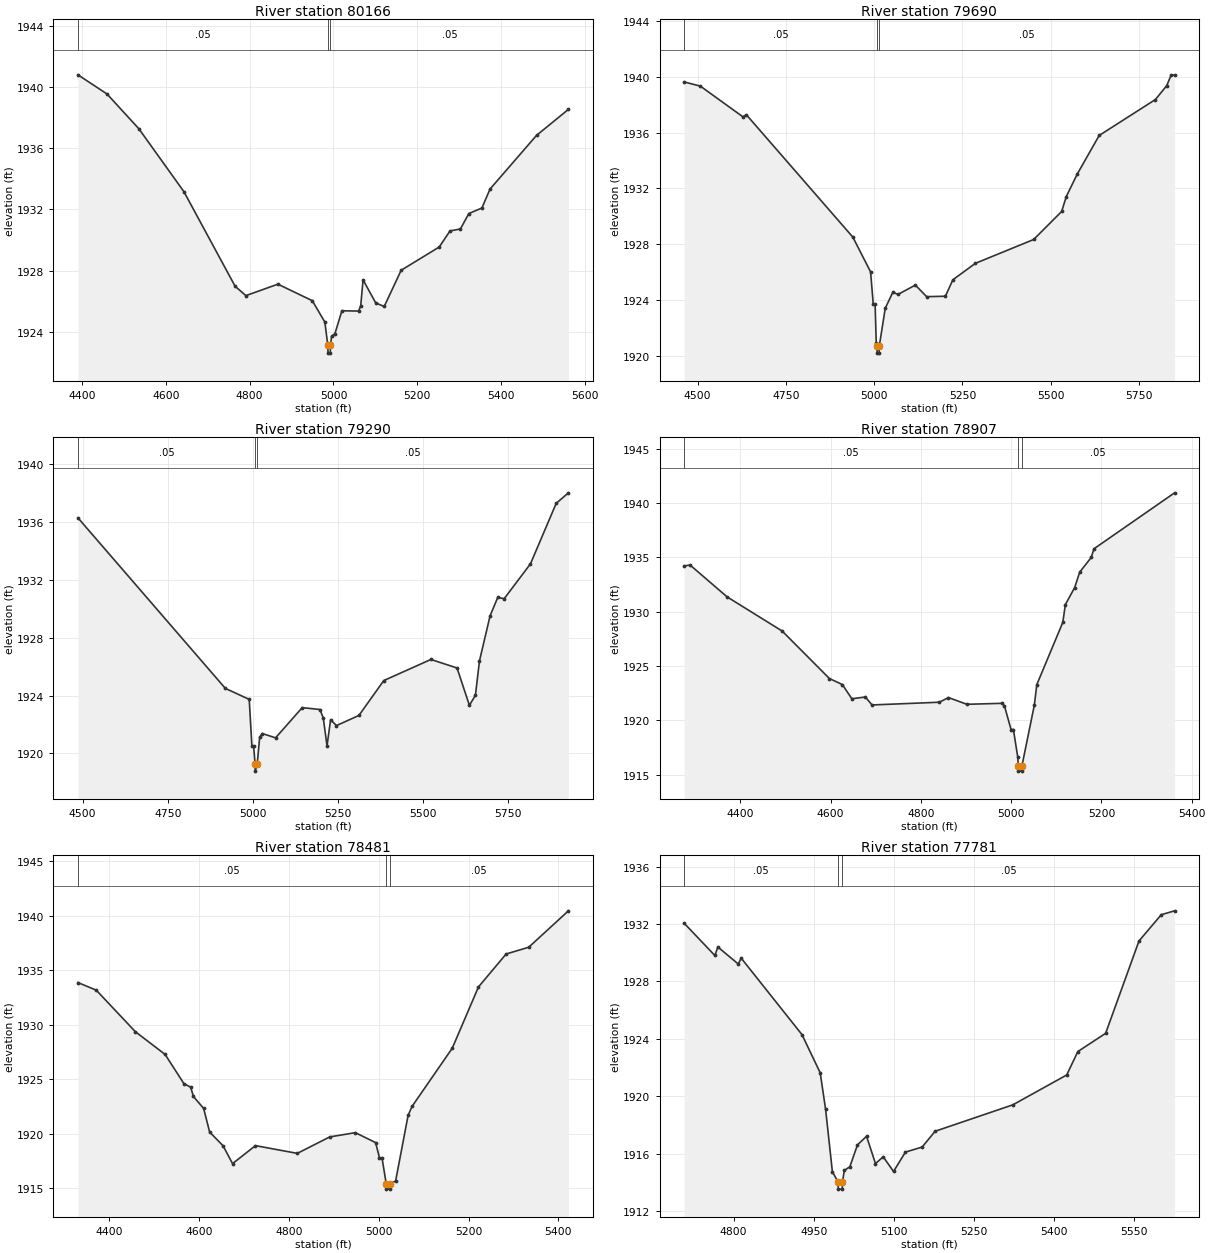
Type RM Length L Ch R = 1 ,80166   ,476,476,476
BEGIN DESCRIPTION:
Buck Creek 80166.27
END DESCRIPTION:
XS GIS Cut Line= 3
      1635957.01      6832881.35      1636558.54      6832761.56
       1637110.3      6832683.49
#Sta/Elev= 30
  4390.1  1940.8  4459.4 1939.55  4535.6 1937.27    4643 1933.16  4765.3 1926.97
    4791 1926.36  4867.3 1927.11  4949.4 1926.03  4979.4 1924.63  4986.5  1923.1
    4987  1922.6  4992.3  1922.6  4992.8  1923.1  4995.4  1923.7  5003.4 1923.87
  5020.1 1925.37    5060 1925.35    5065  1925.7  5070.6 1927.39  5100.9 1925.88
  5121.1 1925.65  5161.5 1928.02  5252.4 1929.54  5278.1 1930.59  5302.9 1930.72
  5323.1 1931.73  5354.2 1932.09  5373.6 1933.33  5484.6 1936.84  5560.7 1938.54
#Mann= 3 ,-1 , 0
  4390.1     .05       0  4986.5     .03       0  4992.8     .05       0
Bank Sta=4986.5,4992.8
XS Rating Curve= 0 ,0
Exp/Cntr=0.3,0.1

Type RM Length L Ch R = 1 ,79690   ,400,400,400
BEGIN DESCRIPTION:
Buck Creek 79690.03
END DESCRIPTION:
XS GIS Cut Line= 3
      1635919.23      6833192.99      1636455.25      6833145.24
      1637256.01      6832858.79
#Sta/Elev= 30
    4462 1939.63    4508 1939.33  4628.4 1937.13  4638.5 1937.27  4939.7  1928.5
  4989.9 1926.01  4997.5 1923.69  5002.7 1923.69    5006 1920.89  5008.2 1920.68
  5008.7 1920.18    5014 1920.18  5014.5 1920.68  5031.5  1923.4    5053 1924.55
  5067.5 1924.39  5116.7 1925.06  5148.6 1924.23  5201.7 1924.26  5222.9 1925.44
  5286.6 1926.62  5451.7 1928.33  5530.9 1930.34    5544 1931.41  5574.8 1933.01
  5637.1 1935.79  5796.4 1938.37  5828.3 1939.36  5841.2 1940.14  5850.6 1940.11
#Mann= 3 ,-1 , 0
    4462     .05       0  5008.2     .05       0  5014.5     .05       0
Bank Sta=5008.2,5014.5
XS Rating Curve= 0 ,0
Exp/Cntr=0.3,0.1

Type RM Length L Ch R = 1 ,79290   ,383,383,383
BEGIN DESCRIPTION:
Buck Creek 79289.83
END DESCRIPTION:
XS GIS Cut Line= 4
      1636042.89      6833395.24      1636555.94      6833421.29
      1636936.15      6833311.91      1637428.31        6833114.
#Sta/Elev= 30
  4486.3 1936.29    4919  1924.5  4989.1 1923.74    4997 1920.49  5002.1 1920.49
  5006.3 1919.28  5006.8 1918.78  5012.6 1919.28  5019.8 1921.13  5027.5 1921.38
  5066.4 1921.08  5144.7 1923.17  5196.7 1923.04  5206.4 1922.46  5217.5 1920.53
    5228 1922.33  5245.3 1921.93  5311.2 1922.63    5384 1925.04  5522.5  1926.5
  5599.2 1925.91  5635.4 1923.33  5653.1 1924.02    5665  1926.4  5696.2 1929.52
  5718.7 1930.79  5737.5  1930.7  5814.7 1933.11  5890.2 1937.29  5926.1 1938.02
#Mann= 3 ,-1 , 0
  4486.3     .05       0  5006.3     .05       0  5012.6     .05       0
Bank Sta=5006.3,5012.6
XS Rating Curve= 0 ,0
Exp/Cntr=0.3,0.1

Type RM Length L Ch R = 1 ,78907   ,426,426,426
BEGIN DESCRIPTION:
Buck Creek 78906.84
END DESCRIPTION:
XS GIS Cut Line= 3
      1636001.91      6833537.17      1636711.54      6833686.91
      1637054.41      6833801.92
#Sta/Elev= 30
  4275.3 1934.21  4288.7 1934.28  4370.4 1931.36  4492.6 1928.21  4597.3 1923.84
  4625.9 1923.29    4647 1921.98    4677 1922.14  4691.7 1921.41    4841 1921.66
    4861 1922.09  4901.9 1921.47  4980.1 1921.56  4985.2 1921.32  4999.8 1919.15
    5005 1919.15  5014.6 1916.63  5015.8 1915.82  5016.3 1915.32  5023.5 1915.32
    5024 1915.82  5051.4 1921.39  5056.9 1923.28  5114.5 1929.01  5120.2 1930.65
  5140.8 1932.21  5151.9 1933.63  5177.6 1934.99  5183.5 1935.78  5362.2 1940.93
#Mann= 3 ,-1 , 0
  4275.3     .05       0  5015.8     .05       0    5024     .05       0
Bank Sta=5015.8,5024
XS Rating Curve= 0 ,0
Exp/Cntr=0.3,0.1

Type RM Length L Ch R = 1 ,78481   ,700,700,700
BEGIN DESCRIPTION:
Buck Creek 78480.54
END DESCRIPTION:
XS GIS Cut Line= 3
      1635882.59      6833632.69      1636440.27      6834005.92
      1636816.15      6834193.86
#Sta/Elev= 30
    4331 1933.87  4371.8 1933.17  4458.8 1929.36  4524.9 1927.28  4566.9 1924.59
  4581.9 1924.27  4587.9 1923.42  4610.7 1922.32    4624 1920.16    4654 1918.89
    4675 1917.26    4726 1918.91  4819.1  1918.2  4891.2 1919.71  4948.2  1920.1
  4993.3 1919.19  5001.9  1917.8  5007.5  1917.8  5016.9 1915.42  5017.4 1914.92
  5024.6 1914.92  5025.1 1915.42  5037.8 1915.66  5065.7  1921.7  5074.4 1922.51
  5163.9 1927.85  5222.2 1933.47  5283.7 1936.49    5334 1937.11  5422.3 1940.45
#Mann= 3 ,-1 , 0
    4331     .05       0  5016.9     .05       0  5025.1     .05       0
Bank Sta=5016.9,5025.1
XS Rating Curve= 0 ,0
Exp/Cntr=0.3,0.1

Type RM Length L Ch R = 1 ,77781   ,623,623,623
BEGIN DESCRIPTION:
Buck Creek 77780.7
END DESCRIPTION:
XS GIS Cut Line= 3
      1635791.51       6833704.3      1635932.14      6833962.98
      1636104.02      6834561.97
#Sta/Elev= 30
  4707.6 1932.06  4765.1 1929.81  4770.8  1930.4  4808.8 1929.22  4814.5 1929.62
  4928.1  1924.3  4962.2 1921.64  4972.3  1919.1    4985 1914.75  4995.6 1914.04
  4996.1 1913.54  5003.4 1913.54  5003.9 1914.04  5007.3 1914.84  5017.7  1915.1
  5031.9 1916.62  5048.9 1917.22  5065.6 1915.32  5080.1 1915.79  5099.4 1914.77
  5121.7 1916.12  5152.9 1916.47  5177.2 1917.57  5322.6 1919.41  5423.4 1921.49
  5444.2 1923.12  5496.2 1924.39  5558.6 1930.82  5600.3 1932.65  5625.2 1932.92
#Mann= 3 ,-1 , 0
  4707.6     .05       0  4995.6     .05       0  5003.9     .05       0
Bank Sta=4995.6,5003.9
XS Rating Curve= 0 ,0
Exp/Cntr=0.3,0.1

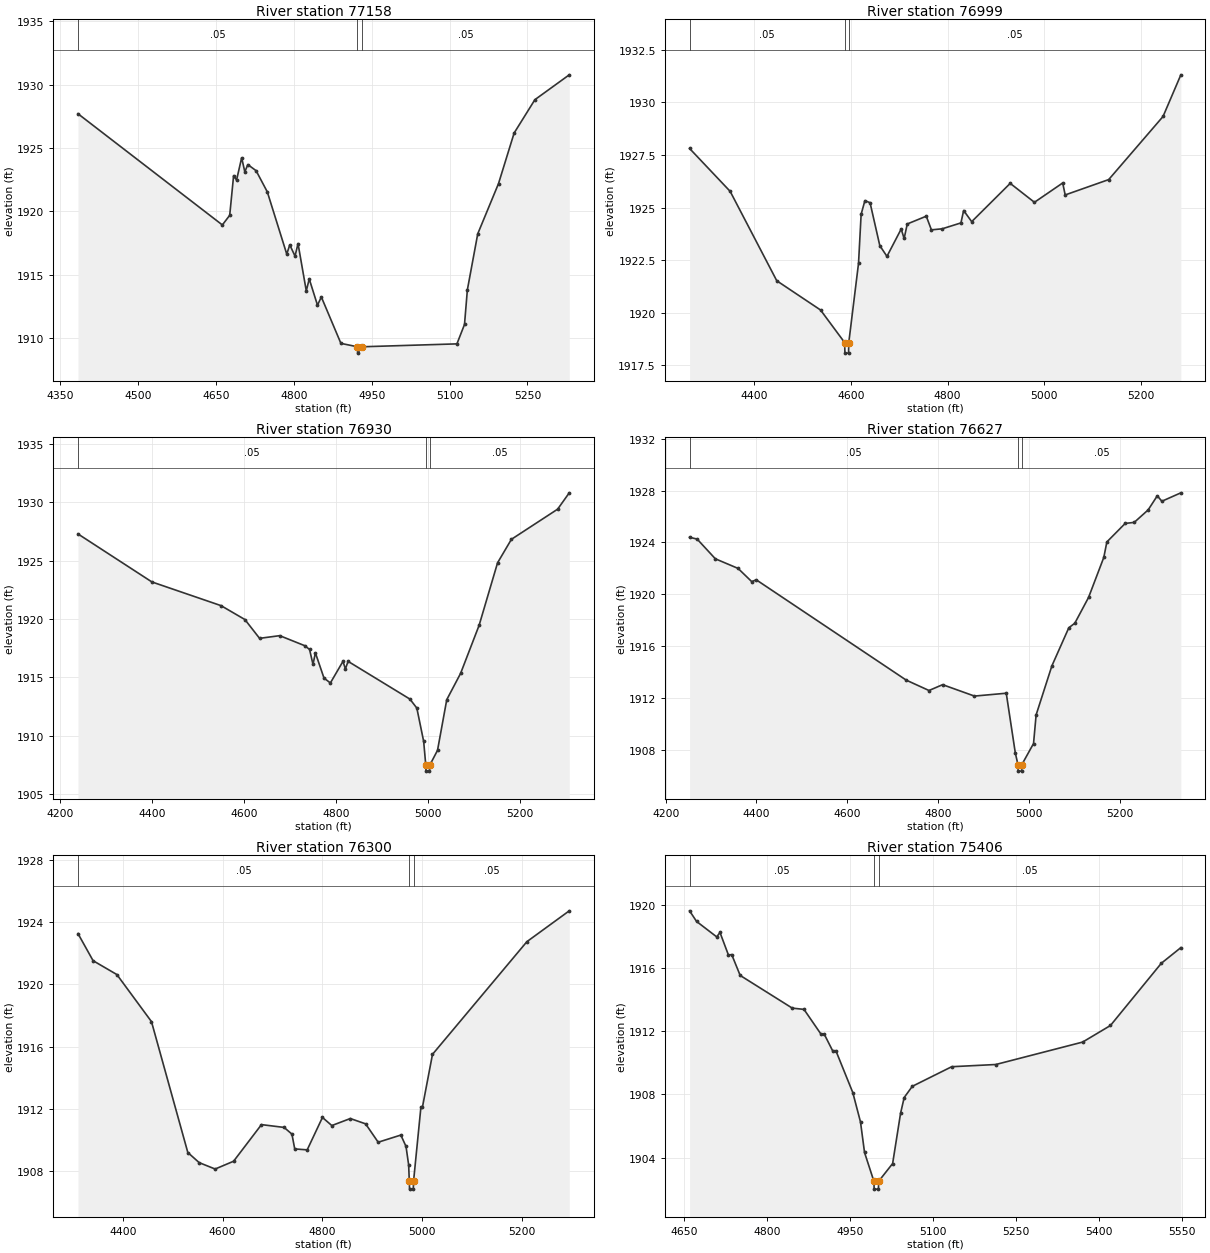
Type RM Length L Ch R = 1 ,77158   ,159,159,159
BEGIN DESCRIPTION:
Buck Creek 77158.17
END DESCRIPTION:
XS GIS Cut Line= 4
      1635798.48      6833853.58      1635567.56      6834261.59
      1635503.32      6834395.27      1635520.63      6834724.08
#Sta/Elev= 30
  4384.1  1927.7  4662.2 1918.93  4676.4 1919.69  4683.9 1922.82  4689.6 1922.47
  4699.4 1924.23  4705.5 1923.12  4711.3 1923.69  4727.2 1923.21  4748.8 1921.54
  4786.3 1916.63  4792.1 1917.36  4802.2 1916.47    4808 1917.46  4823.9 1913.73
  4829.6 1914.67  4845.5  1912.6  4852.9 1913.25  4890.6 1909.59  4922.4 1909.32
  4922.9 1908.82  4930.9 1909.32  5114.1 1909.55  5128.7 1911.08  5134.2 1913.81
  5154.2 1918.23  5194.2 1922.19  5224.3 1926.18  5264.3 1928.81  5330.5 1930.77
#Mann= 3 ,-1 , 0
  4384.1     .05       0  4922.4     .03       0  4930.9     .05       0
Bank Sta=4922.4,4930.9
XS Rating Curve= 0 ,0
Exp/Cntr=0.3,0.1

Type RM Length L Ch R = 1 ,76999   ,69,69,69
BEGIN DESCRIPTION:
Buck Creek 76999.3
END DESCRIPTION:
XS GIS Cut Line= 6
      1635678.67      6833839.71      1635538.04      6834199.09
      1635452.97      6834259.86        1635387.      6834390.07
      1635380.06      6834487.29      1635447.74      6834763.21
#Sta/Elev= 30
  4265.5 1927.81  4349.6 1925.77  4446.2 1921.52  4536.9 1920.13  4586.9 1918.58
  4587.4 1918.08  4594.9 1918.08  4595.4 1918.58  4615.6 1922.35    4621 1924.68
  4628.8 1925.33  4639.5 1925.23  4659.7 1923.19  4674.5 1922.68    4704 1923.98
  4710.1 1923.53  4716.6 1924.22    4756 1924.59  4766.6 1923.94  4788.9 1923.99
  4827.8 1924.27  4833.4 1924.86  4850.1 1924.33  4929.9 1926.15  4980.1 1925.25
  5038.7 1926.17  5043.8  1925.6    5134 1926.33  5246.6 1929.33  5283.5 1931.31
#Mann= 3 ,-1 , 0
  4265.5     .05       0  4586.9     .05       0  4595.4     .05       0
Bank Sta=4586.9,4595.4
XS Rating Curve= 0 ,0
Exp/Cntr=0.3,0.1

Type RM Length L Ch R = 1 ,76930   ,303,303,303
BEGIN DESCRIPTION:
Buck Creek 76929.65
END DESCRIPTION:
XS GIS Cut Line= 5
      1635565.83      6833777.21      1635367.91      6834221.66
      1635308.88      6834412.63      1635310.61      6834490.76
      1635339.99      6834793.17
#Sta/Elev= 30
  4238.5 1927.29  4399.2 1923.18  4549.6 1921.15  4601.5 1919.96  4633.4 1918.35
  4677.2 1918.58  4731.7 1917.72  4742.1  1917.4  4749.6 1916.12  4754.8 1917.11
  4773.5 1914.95  4787.4 1914.53  4814.8 1916.38  4820.1 1915.73  4825.9 1916.38
  4960.3 1913.15  4975.4 1912.38  4990.3 1909.52  4994.9 1907.48  4995.4 1906.98
  5002.9 1906.98  5003.4 1907.48  5020.4 1908.76  5040.5  1913.1  5070.6 1915.35
  5110.8 1919.46    5151 1924.82  5181.1 1926.83  5281.6 1929.41  5306.9 1930.81
#Mann= 3 ,-1 , 0
  4238.5     .05       0  4994.9     .05       0  5003.4     .05       0
Bank Sta=4994.9,5003.4
XS Rating Curve= 0 ,0
Exp/Cntr=0.3,0.1

Type RM Length L Ch R = 1 ,76627   ,327,327,327
BEGIN DESCRIPTION:
Buck Creek 76626.54
END DESCRIPTION:
XS GIS Cut Line= 3
      1635000.02      6833841.29      1635038.22      6834591.28
      1635083.36      6834919.43
#Sta/Elev= 30
  4252.7  1924.4  4269.4 1924.26  4309.5 1922.74  4359.5    1922  4389.6 1920.98
  4399.6 1921.12    4730 1913.38  4780.1 1912.58  4810.1 1913.03  4880.2 1912.15
  4950.3 1912.37  4970.3 1907.75  4976.1 1906.86  4976.6 1906.36  4984.1 1906.36
  4984.6 1906.86  5010.4 1908.49  5016.1  1910.7  5050.8 1914.48  5088.1 1917.42
  5101.3 1917.77  5131.6 1919.76  5165.2 1922.85  5171.9 1924.04  5212.3 1925.47
  5232.2 1925.55  5262.8 1926.51    5283  1927.6  5293.1 1927.18  5334.9 1927.83
#Mann= 3 ,-1 , 0
  4252.7     .05       0  4976.1     .05       0  4984.6     .05       0
Bank Sta=4976.1,4984.6
XS Rating Curve= 0 ,0
Exp/Cntr=0.3,0.1

Type RM Length L Ch R = 1 ,76300   ,894,894,894
BEGIN DESCRIPTION:
Buck Creek 76300.45
END DESCRIPTION:
XS GIS Cut Line= 3
      1634543.41      6834089.51      1634779.54      6834738.85
      1634866.35      6835020.12
#Sta/Elev= 30
  4309.8 1923.26  4340.1 1921.52  4387.8 1920.63  4457.2 1917.61  4530.1 1909.21
  4552.9 1908.56  4584.9 1908.15  4621.9 1908.65  4677.8    1911  4723.2 1910.82
  4738.9 1910.39  4744.5 1909.44  4769.5 1909.38  4800.1 1911.46  4818.9 1910.94
    4856 1911.39  4886.6 1911.05  4911.9 1909.87  4957.3 1910.33  4967.7  1909.6
    4973 1908.41  4974.3 1907.36  4974.8 1906.86  4982.3 1906.86  4982.8 1907.36
  4997.6 1912.13  5000.7 1912.13  5020.8 1915.51  5210.1 1922.74  5295.1 1924.72
#Mann= 3 ,-1 , 0
  4309.8     .05       0  4974.3     .05       0  4982.8     .05       0
Bank Sta=4974.3,4982.8
XS Rating Curve= 0 ,0
Exp/Cntr=0.3,0.1

Type RM Length L Ch R = 1 ,75406   ,347,347,347
BEGIN DESCRIPTION:
Buck Creek 75405.54
END DESCRIPTION:
XS GIS Cut Line= 3
      1634030.81      6834306.32       1634213.1      6834596.26
      1634532.54      6835038.96
#Sta/Elev= 30
  4660.2 1919.62  4672.8 1918.95  4709.3 1917.97  4715.2 1918.25  4730.5 1916.82
  4736.4 1916.85  4751.7 1915.53  4845.9 1913.46  4867.1 1913.38  4897.7 1911.82
  4903.6 1911.82  4918.9 1910.76  4924.8 1910.76  4955.4 1908.11  4969.3 1906.25
  4976.6 1904.32  4993.5  1902.5    4994    1902  5001.7    1902  5002.2  1902.5
  5027.4 1903.62  5041.8 1906.81  5048.3  1907.8    5063 1908.51  5134.2 1909.75
  5213.9 1909.89    5371 1911.31  5421.3 1912.36  5513.3  1916.3  5548.6 1917.29
#Mann= 3 ,-1 , 0
  4660.2     .05       0  4993.5     .05       0  5002.2     .05       0
Bank Sta=4993.5,5002.2
XS Rating Curve= 0 ,0
Exp/Cntr=0.3,0.1

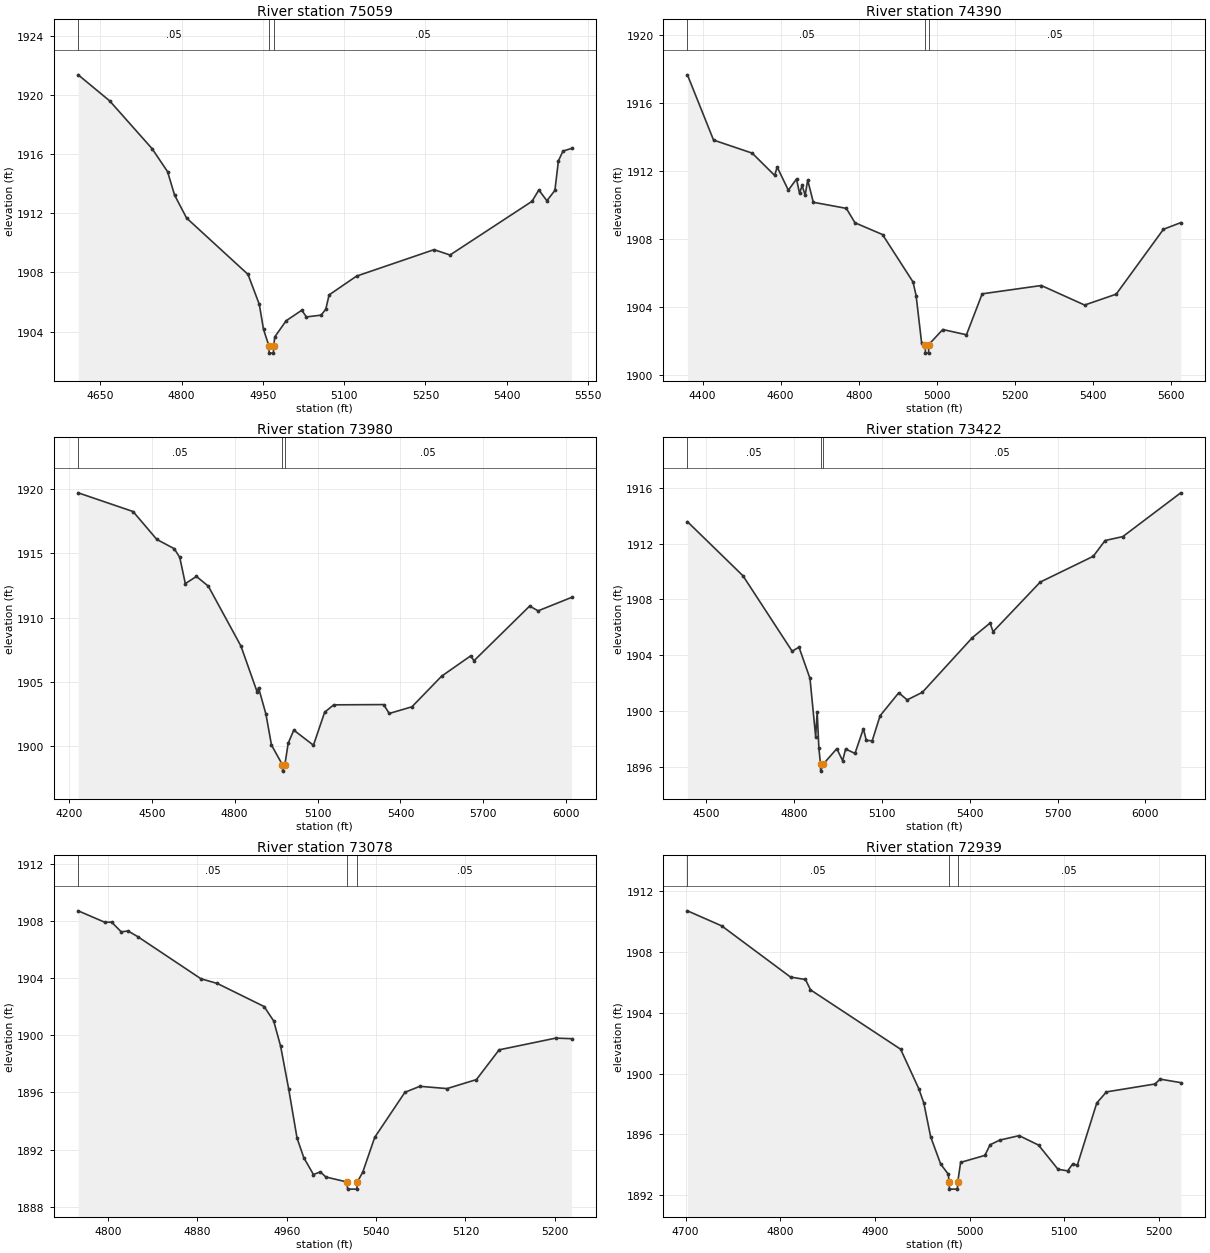
Type RM Length L Ch R = 1 ,75059   ,669,669,669
BEGIN DESCRIPTION:
Buck Creek 75059.07
END DESCRIPTION:
XS GIS Cut Line= 3
      1633700.92      6834490.85      1633948.32      6834790.33
      1634247.78      6835217.83
#Sta/Elev= 30
  4609.1 1921.37  4667.1 1919.61  4745.3 1916.38    4774 1914.82    4787 1913.23
  4809.1 1911.68  4922.4 1907.87  4943.3 1905.84  4951.1 1904.14    4961 1903.04
  4961.5 1902.54  4969.3 1902.54  4969.8 1903.04  4971.9 1903.64  4992.8 1904.73
  5021.6 1905.44  5030.3 1904.99  5057.3 1905.11    5066 1905.51  5072.1 1906.48
  5122.7 1907.75  5265.7 1909.54  5295.3 1909.18  5446.5 1912.81  5459.2 1913.58
    5474 1912.85  5488.8 1913.55  5495.3 1915.55  5503.7 1916.21  5519.5 1916.39
#Mann= 3 ,-1 , 0
  4609.1     .05       0    4961     .05       0  4969.8     .05       0
Bank Sta=4961,4969.8
XS Rating Curve= 0 ,0
Exp/Cntr=0.3,0.1

Type RM Length L Ch R = 1 ,74390   ,410,410,410
BEGIN DESCRIPTION:
Buck Creek 74389.79
END DESCRIPTION:
XS GIS Cut Line= 3
      1632954.58       6834534.8      1633362.56      6835029.58
      1633978.88      6835112.05
#Sta/Elev= 30
  4361.4 1917.67  4428.3 1913.83  4527.3 1913.06  4584.7 1911.75  4591.2 1912.24
  4619.8 1910.88  4640.7 1911.54  4648.5 1910.69    4655 1911.16  4662.9 1910.58
  4669.3 1911.48  4683.7 1910.17  4768.3 1909.81  4790.5 1908.96  4860.9 1908.27
    4939 1905.48  4946.9 1904.68  4961.2 1901.86  4970.3 1901.79  4970.8 1901.29
  4978.7 1901.29  4979.2 1901.79  5015.2 1902.68  5075.8 1902.37  5116.1 1904.78
  5267.5 1905.27  5378.4 1904.12  5459.2 1904.76  5580.2 1908.58  5624.5 1908.97
#Mann= 3 ,-1 , 0
  4361.4     .05       0  4970.3     .05       0  4979.2     .05       0
Bank Sta=4970.3,4979.2
XS Rating Curve= 0 ,0
Exp/Cntr=0.3,0.1

Type RM Length L Ch R = 1 ,73980   ,558,558,558
BEGIN DESCRIPTION:
Buck Creek 73980.2
END DESCRIPTION:
XS GIS Cut Line= 3
      1632359.79      6835404.47      1633125.83      6835319.84
      1634124.11      6835139.72
#Sta/Elev= 30
  4233.9 1919.67  4432.4 1918.22  4518.2 1916.06  4581.2 1915.34  4601.3 1914.67
  4621.5 1912.63  4661.7 1913.19  4704.8 1912.43  4822.7 1907.79  4881.4 1904.23
  4886.4 1904.56  4913.2 1902.51  4933.3 1900.11  4972.7 1898.59  4973.2 1898.09
  4981.7 1898.59  4993.7 1900.25  5013.9 1901.27  5085.1  1900.1  5125.7 1902.66
  5158.5 1903.23  5339.1 1903.25  5359.4 1902.56  5441.6 1903.08  5548.7 1905.45
  5654.1 1907.03    5666 1906.65  5867.5 1910.89    5898 1910.52    6019 1911.56
#Mann= 3 ,-1 , 0
  4233.9     .05       0  4972.7     .03       0  4981.7     .05       0
Bank Sta=4972.7,4981.7
XS Rating Curve= 0 ,0
Exp/Cntr=0.3,0.1

Type RM Length L Ch R = 1 ,73422   ,344,344,344
BEGIN DESCRIPTION:
Buck Creek 73422.21
END DESCRIPTION:
XS GIS Cut Line= 3
       1632312.2      6835862.92      1632880.79      6835771.77
      1633981.63      6835654.75
#Sta/Elev= 30
  4437.4 1913.58    4627  1909.7  4794.7 1904.29    4818 1904.58  4855.5 1902.34
  4874.9 1898.15    4880 1899.94  4885.9 1897.32  4891.4 1896.19  4891.9 1895.69
  4900.6 1896.19    4947  1897.3  4966.9 1896.44    4977 1897.28    5009 1896.96
  5037.6 1898.73  5047.7 1897.89  5067.8 1897.87  5094.6 1899.66  5158.3 1901.31
  5187.1  1900.8  5238.7 1901.34  5409.7 1905.27  5469.8 1906.31  5480.1 1905.69
    5641 1909.25    5822  1911.1  5862.2 1912.23  5922.6 1912.51  6120.3 1915.65
#Mann= 3 ,-1 , 0
  4437.4     .05       0  4891.4     .05       0  4900.6     .05       0
Bank Sta=4891.4,4900.6
XS Rating Curve= 0 ,0
Exp/Cntr=0.3,0.1

Type RM Length L Ch R = 1 ,73078   ,139,139,139
BEGIN DESCRIPTION:
Buck Creek 73077.95
END DESCRIPTION:
XS GIS Cut Line= 4
      1632471.75      6835888.43      1632654.05      6836018.65
       1632723.5      6836027.33      1632868.93       6836051.2
#Sta/Elev= 30
  4773.5  1908.7  4797.3  1907.9  4803.4 1907.91    4812 1907.23  4818.1 1907.29
  4826.7  1906.9  4883.3 1903.95    4898 1903.62  4939.8 1902.01  4948.4    1901
  4954.6 1899.24  4961.8 1896.25  4969.3 1892.81  4975.4 1891.43    4984 1890.26
  4990.2 1890.45    4995 1890.09    5014 1889.74  5014.5 1889.24  5022.8 1889.24
  5023.3 1889.74  5028.2 1890.45  5038.8 1892.86  5065.8 1896.01  5079.2 1896.43
  5103.5 1896.27  5129.8  1896.9  5150.1 1898.98  5200.8  1899.8  5214.9 1899.76
#Mann= 3 ,-1 , 0
  4773.5     .05       0    5014     .05       0  5023.3     .05       0
Bank Sta=5014,5023.3
XS Rating Curve= 0 ,0
Exp/Cntr=0.3,0.1

Type RM Length L Ch R = 1 ,72939   ,316,316,316
BEGIN DESCRIPTION:
Buck Creek 72938.89
END DESCRIPTION:
XS GIS Cut Line= 3
      1632322.03      6836042.52      1632606.31      6836140.17
      1632821.68      6836187.55
#Sta/Elev= 30
  4701.9 1910.71  4738.1 1909.72  4810.8 1906.35  4826.6 1906.19  4831.9 1905.51
  4927.1  1901.6  4946.3    1899  4951.6 1898.06  4958.8 1895.84  4969.4 1894.04
  4977.5 1893.37  4978.2 1892.89  4978.7 1892.39    4987 1892.39  4987.5 1892.89
  4990.5 1894.15  5016.1 1894.61  5021.6 1895.31  5031.9 1895.62  5052.3 1895.91
  5072.8 1895.29  5093.3  1893.7  5103.5 1893.59  5108.7 1894.03  5113.8 1893.98
  5134.3 1898.06  5144.5 1898.79  5195.7 1899.31  5201.3 1899.63    5223  1899.4
#Mann= 3 ,-1 , 0
  4701.9     .05       0  4978.2     .05       0  4987.5     .05       0
Bank Sta=4978.2,4987.5
XS Rating Curve= 0 ,0
Exp/Cntr=0.3,0.1