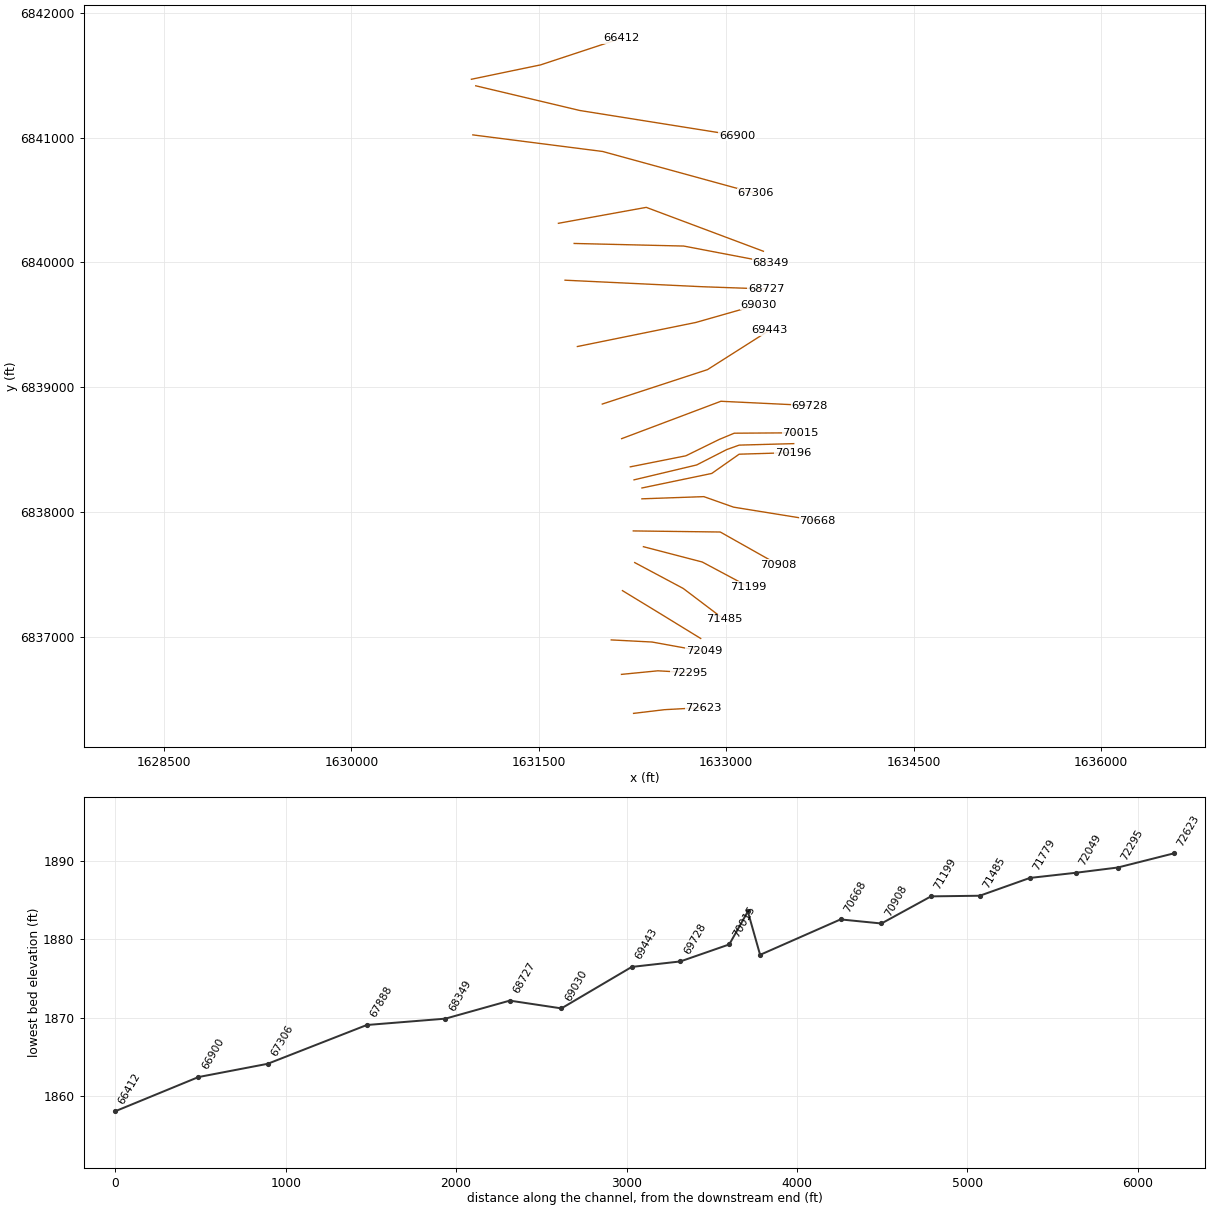
HEC-RAS study Buck Creek.prj: Buck Creek Base Level Engineering

--- Buck Creek.g01 (geometry) --- (continued)

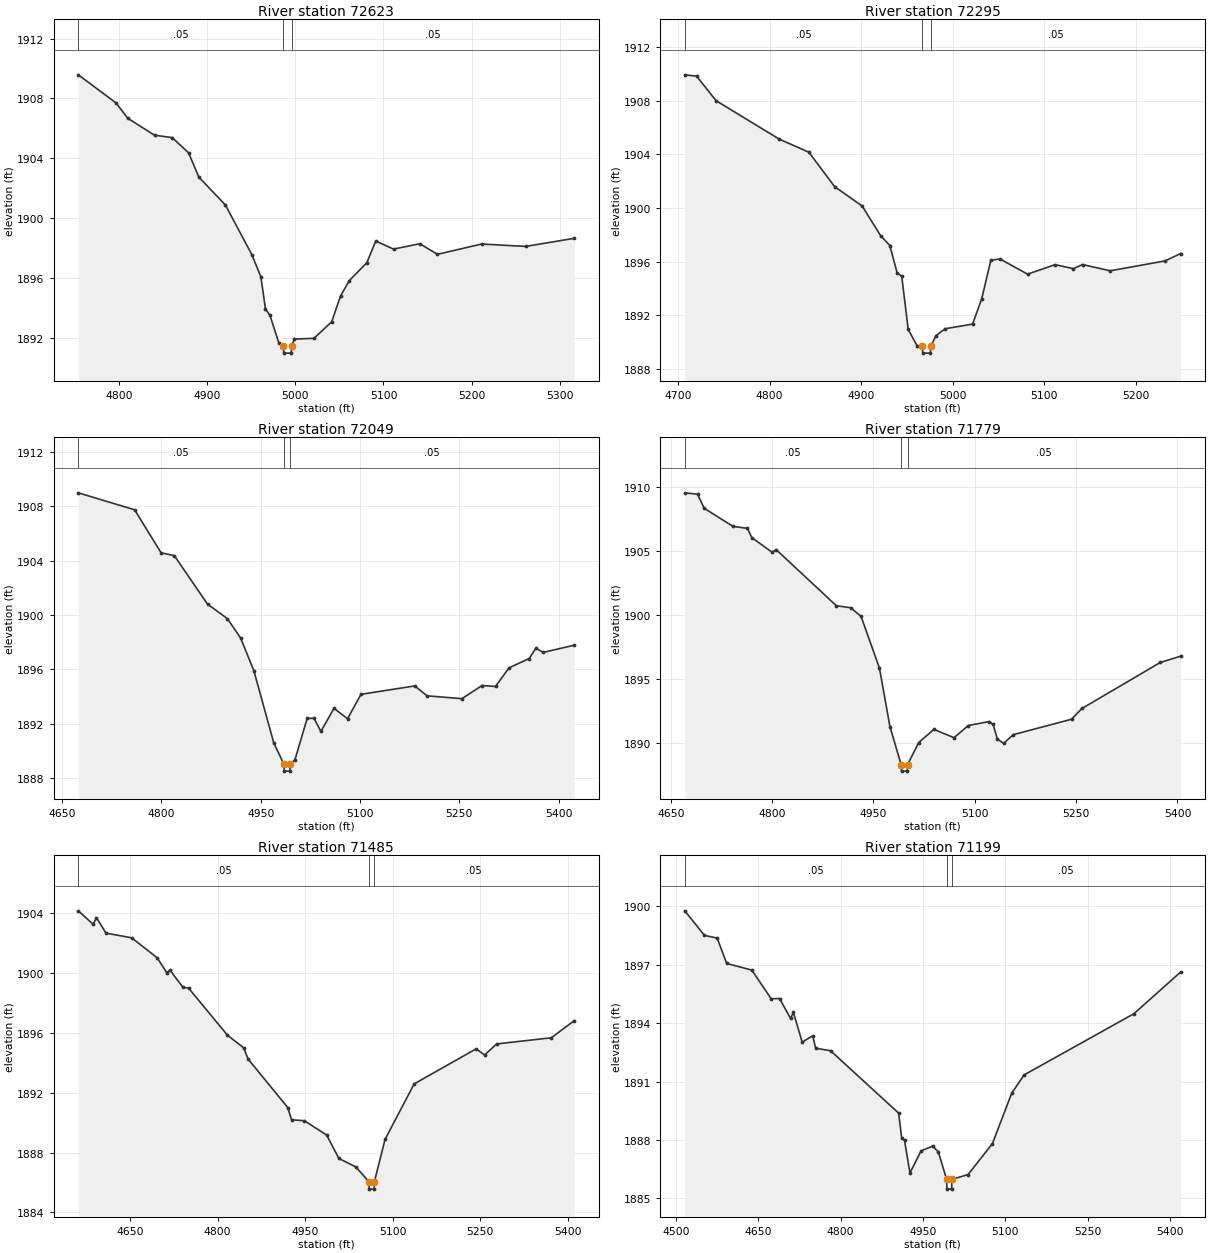
Type RM Length L Ch R = 1 ,72623   ,328,328,328
BEGIN DESCRIPTION:
Buck Creek 72622.5
END DESCRIPTION:
XS GIS Cut Line= 3
      1632259.16      6836387.71       1632505.7      6836417.23
      1632819.92      6836434.59
#Sta/Elev= 30
  4753.5 1909.58  4796.3  1907.7  4809.7 1906.67    4840 1905.54  4860.1 1905.38
  4878.7 1904.36  4890.3 1902.74  4920.5 1900.87  4950.7 1897.53  4960.8 1896.06
    4966 1893.91  4971.1 1893.49    4981 1891.67  4986.4 1891.46  4986.9 1890.96
  4995.2 1890.96  4995.7 1891.46  4998.9  1891.9  5021.1 1891.95  5041.2 1893.06
  5051.2 1894.78  5061.2 1895.81  5081.2 1897.02  5091.2 1898.46  5111.4 1897.92
  5141.3 1898.28  5161.3 1897.57  5211.4 1898.26  5261.5  1898.1  5316.5 1898.64
#Mann= 3 ,-1 , 0
  4753.5     .05       0  4986.4     .05       0  4995.7     .05       0
Bank Sta=4986.4,4995.7
XS Rating Curve= 0 ,0
Exp/Cntr=0.3,0.1

Type RM Length L Ch R = 1 ,72295   ,246,246,246
BEGIN DESCRIPTION:
Buck Creek 72295.15
END DESCRIPTION:
XS GIS Cut Line= 3
      1632162.19      6836700.04      1632453.84      6836728.69
      1632701.88      6836714.48
#Sta/Elev= 30
  4707.3 1909.95  4720.2 1909.85  4741.4 1908.02  4810.6 1905.14  4842.8 1904.17
  4870.9  1901.6    4901 1900.15  4921.1 1897.94  4931.2  1897.2  4939.2 1895.15
  4944.2 1894.91  4951.3 1890.93  4961.3 1889.67  4966.7 1889.66  4967.2 1889.16
  4975.5 1889.16    4976 1889.66  4981.4 1890.45  4991.5 1890.98  5021.6 1891.33
  5031.6 1893.23  5041.6 1896.11  5051.6 1896.19  5081.7 1895.06  5111.7 1895.77
  5131.7 1895.47  5141.7 1895.78  5171.8 1895.31  5231.9 1896.05  5248.8  1896.6
#Mann= 3 ,-1 , 0
  4707.3     .05       0  4966.7     .05       0    4976     .05       0
Bank Sta=4966.7,4976
XS Rating Curve= 0 ,0
Exp/Cntr=0.3,0.1

Type RM Length L Ch R = 1 ,72049   ,270,270,270
BEGIN DESCRIPTION:
Buck Creek 72049.01
END DESCRIPTION:
XS GIS Cut Line= 3
      1632080.16      6836976.08      1632406.96      6836959.16
      1632821.86      6836883.95
#Sta/Elev= 30
  4674.6    1909  4759.6 1907.75  4799.6 1904.58  4819.6 1904.37  4869.7  1900.8
  4899.7 1899.73  4919.8 1898.29  4939.8 1895.88  4969.8 1890.57  4985.2 1888.99
  4985.7 1888.49  4994.1 1888.49  4994.6 1888.99  5001.8 1889.33  5020.2 1892.37
  5030.3 1892.39    5041 1891.42  5060.8 1893.12  5081.2 1892.35  5101.5 1894.15
  5182.8 1894.77  5201.3 1894.04  5253.9 1893.83  5284.4  1894.8  5304.7 1894.73
  5325.1  1896.1  5355.6 1896.79  5365.7 1897.55  5376.9 1897.24  5423.5 1897.77
#Mann= 3 ,-1 , 0
  4674.6     .05       0  4985.2     .05       0  4994.6     .05       0
Bank Sta=4985.2,4994.6
XS Rating Curve= 0 ,0
Exp/Cntr=0.3,0.1

Type RM Length L Ch R = 1 ,71779   ,294,294,294
BEGIN DESCRIPTION:
Buck Creek 71778.64
END DESCRIPTION:
XS GIS Cut Line= 3
       1632170.2      6837370.72       1632453.4       6837198.2
      1632796.32      6836987.67
#Sta/Elev= 30
  4670.7 1909.55  4689.7 1909.44  4699.3 1908.35    4742 1906.93  4763.3 1906.78
    4770 1906.05  4800.1 1904.91  4805.9 1905.12    4895 1900.74  4916.3 1900.58
  4931.7  1899.9  4958.9 1895.86  4974.4  1891.3    4991 1888.33  4991.5 1887.83
  4999.9 1887.83  5000.4 1888.33    5017 1890.06  5039.4 1891.09  5069.2 1890.44
  5090.4 1891.39  5121.3  1891.7  5127.2 1891.47  5133.3 1890.35  5142.6 1889.99
  5156.7 1890.67  5243.2 1891.88  5258.6 1892.72  5374.6 1896.31  5404.7  1896.8
#Mann= 3 ,-1 , 0
  4670.7     .05       0    4991     .05       0  5000.4     .05       0
Bank Sta=4991,5000.4
XS Rating Curve= 0 ,0
Exp/Cntr=0.3,0.1

Type RM Length L Ch R = 1 ,71485   ,286,286,286
BEGIN DESCRIPTION:
Buck Creek 71484.55
END DESCRIPTION:
XS GIS Cut Line= 3
      1632268.33      6837595.39      1632656.36      6837388.35
      1632983.17      6837140.97
#Sta/Elev= 30
  4561.2 1904.15  4586.6 1903.25  4592.3 1903.69  4608.6 1902.66  4652.5 1902.35
  4696.4 1901.01  4712.7 1900.02  4718.4 1900.18  4740.3 1899.05  4750.1 1898.99
  4816.8 1895.84  4844.5    1895  4852.1 1894.25  4920.1 1891.01  4926.6 1890.19
  4948.6 1890.13  4986.8 1889.17  5007.7 1887.61  5036.8 1887.04  5059.2 1886.06
  5059.7 1885.56  5068.1 1885.56  5068.6 1886.06  5086.8 1888.88  5136.7 1892.59
  5242.9 1894.93  5257.4 1894.52  5278.2 1895.26  5371.8 1895.67  5410.9 1896.81
#Mann= 3 ,-1 , 0
  4561.2     .05       0  5059.2     .05       0  5068.6     .05       0
Bank Sta=5059.2,5068.6
XS Rating Curve= 0 ,0
Exp/Cntr=0.3,0.1

Type RM Length L Ch R = 1 ,71199   ,291,291,291
BEGIN DESCRIPTION:
Buck Creek 71198.89
END DESCRIPTION:
XS GIS Cut Line= 3
       1632337.9      6837722.69      1632808.78      6837600.09
      1633176.65      6837403.68
#Sta/Elev= 30
    4516 1899.76  4551.8  1898.5    4575 1898.36  4592.3 1897.06    4638 1896.72
  4673.4 1895.25  4688.7 1895.26  4708.7 1894.24  4713.9 1894.55    4730 1893.02
  4749.2 1893.35  4754.4 1892.71  4781.7 1892.58  4905.7 1889.38  4911.2 1888.11
  4916.4 1887.99  4926.3 1886.31  4946.6 1887.44  4967.7 1887.69    4978 1887.39
  4993.2 1885.98  4993.7 1885.48  5002.3 1885.48  5002.8 1885.98  5032.3 1886.23
  5076.7 1887.82  5111.7  1890.4  5134.3 1891.34  5334.4 1894.48  5419.6 1896.62
#Mann= 3 ,-1 , 0
    4516     .05       0  4993.2     .05       0  5002.8     .05       0
Bank Sta=4993.2,5002.8
XS Rating Curve= 0 ,0
Exp/Cntr=0.3,0.1

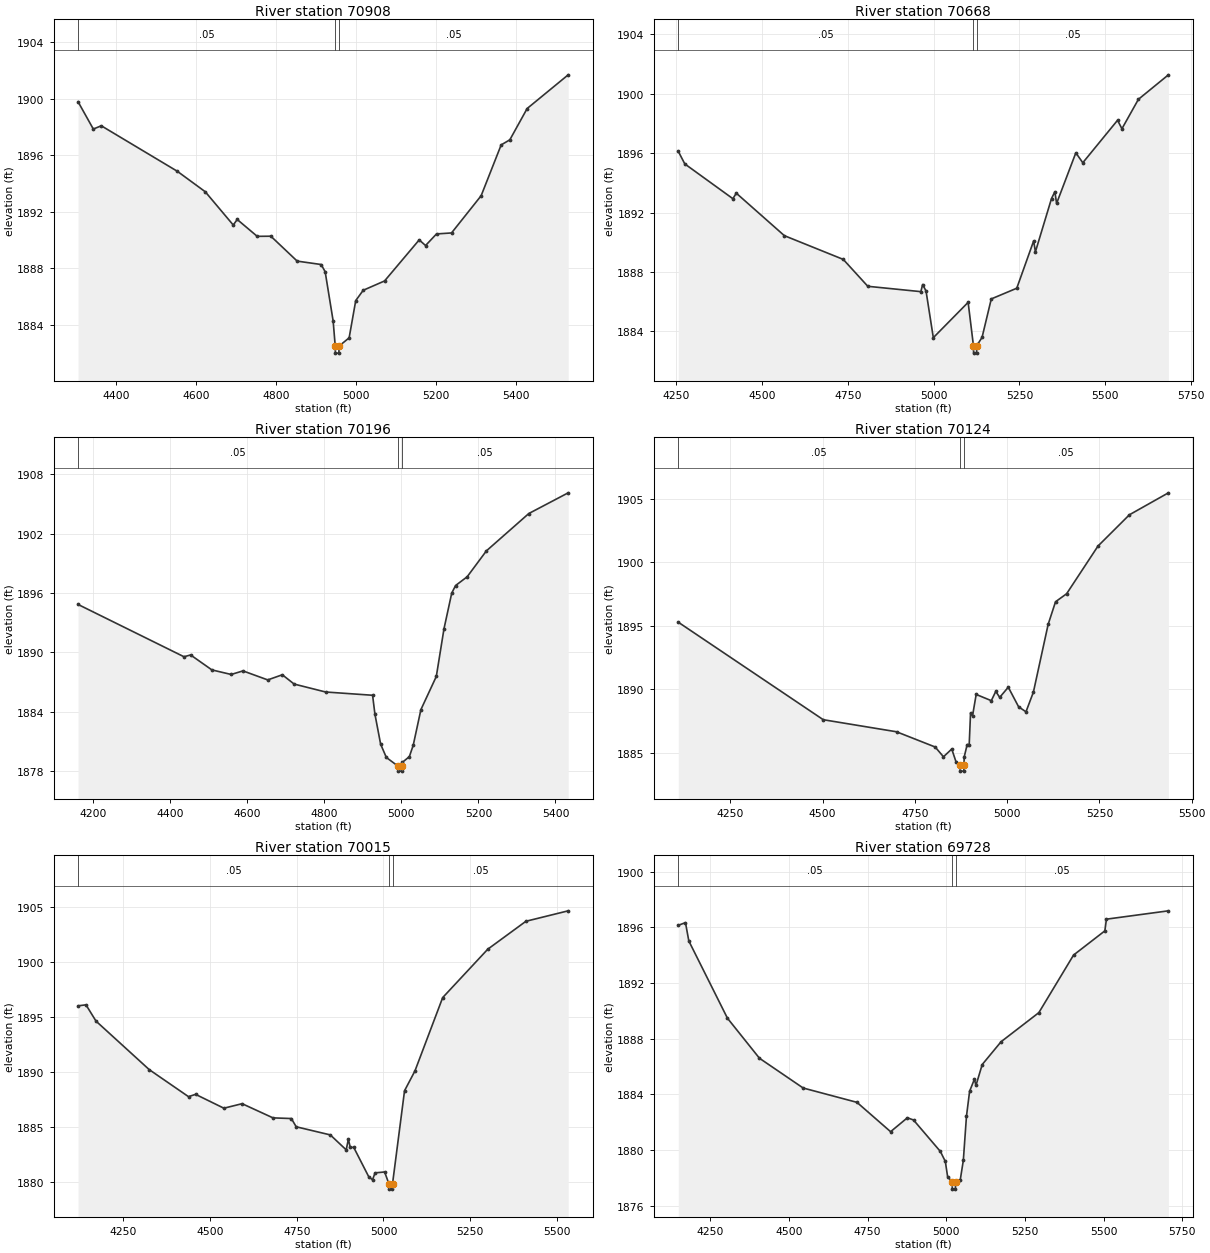
Type RM Length L Ch R = 1 ,70908   ,240,240,240
BEGIN DESCRIPTION:
Buck Creek 70908.06
END DESCRIPTION:
XS GIS Cut Line= 3
      1632256.77        6837849.      1632952.95      6837840.32
      1633414.75      6837579.91
#Sta/Elev= 30
  4305.2 1899.78  4343.4 1897.85  4363.4 1898.08  4553.4 1894.87  4623.5 1893.42
  4693.5 1891.07  4703.5 1891.46  4753.5 1890.27  4787.6 1890.28  4853.5 1888.52
  4913.5 1888.28  4923.5 1887.77  4943.5 1884.29  4948.7 1882.52  4949.2 1882.02
  4957.8 1882.02  4958.3 1882.52  4983.5  1883.1    5000 1885.73  5018.7 1886.46
  5072.2 1887.12  5158.8 1890.02  5174.7 1889.62  5202.1 1890.44  5239.7 1890.51
  5313.8 1893.14  5363.9 1896.73  5385.6 1897.09  5428.9  1899.3  5531.6 1901.68
#Mann= 3 ,-1 , 0
  4305.2     .05       0  4948.7     .05       0  4958.3     .05       0
Bank Sta=4948.7,4958.3
XS Rating Curve= 0 ,0
Exp/Cntr=0.3,0.1

Type RM Length L Ch R = 1 ,70668   ,472,472,472
BEGIN DESCRIPTION:
Buck Creek 70668.34
END DESCRIPTION:
XS GIS Cut Line= 4
      1632325.86      6838106.17      1632821.47      6838123.64
      1633059.99      6838039.32      1633731.41      6837931.03
#Sta/Elev= 30
  4255.2 1896.13  4274.3 1895.28  4414.4 1892.94  4424.4 1893.31  4564.5 1890.45
  4736.3 1888.85  4807.8 1887.04  4962.4 1886.68  4967.7 1887.16  4977.6 1886.72
  4998.8 1883.58  5100.3 1885.96  5115.8 1883.04  5116.3 1882.54  5124.9 1882.54
  5125.4 1883.04  5140.9  1883.6  5167.8 1886.19  5242.1 1886.91  5291.4  1890.1
  5296.4 1889.36  5343.4 1892.95  5353.2 1893.41  5358.2 1892.62  5414.3 1896.03
  5434.6 1895.36  5535.9 1898.22  5548.7 1897.65  5596.7 1899.63  5684.2 1901.28
#Mann= 3 ,-1 , 0
  4255.2     .05       0  5115.8     .05       0  5125.4     .05       0
Bank Sta=5115.8,5125.4
XS Rating Curve= 0 ,0
Exp/Cntr=0.3,0.1

Type RM Length L Ch R = 1 ,70196   ,72,72,72
BEGIN DESCRIPTION:
Buck Creek 70196.39
END DESCRIPTION:
XS GIS Cut Line= 4
       1632325.9      6838192.98      1632884.76      6838309.42
      1633104.19      6838463.59      1633537.16      6838476.61
#Sta/Elev= 30
  4160.8 1894.85  4435.7 1889.57    4453 1889.75  4508.2 1888.24  4558.3 1887.78
  4588.9 1888.14  4653.2 1887.23    4691 1887.75  4721.7 1886.81  4803.3 1886.01
  4925.3 1885.68  4931.4 1883.76  4946.2 1880.74    4961  1879.4  4991.4 1878.52
  4991.9 1878.02  5001.6 1878.02  5002.1 1878.52  5002.7 1878.91  5020.7 1879.48
  5030.7 1880.62  5050.7 1884.23  5090.7 1887.58  5110.7 1892.41  5130.7 1895.99
  5140.7 1896.76  5170.7 1897.64  5220.7 1900.26  5330.8 1904.03    5433 1906.12
#Mann= 3 ,-1 , 0
  4160.8     .05       0  4991.4     .05       0  5002.1     .05       0
Bank Sta=4991.4,5002.1
XS Rating Curve= 0 ,0
Exp/Cntr=0.3,0.1

Type RM Length L Ch R = 1 ,70124   ,109,109,109
BEGIN DESCRIPTION:
Buck Creek 70123.8
END DESCRIPTION:
XS GIS Cut Line= 5
      1632262.89      6838258.07      1632764.21      6838377.48
      1633004.36      6838500.48      1633104.19      6838536.29
      1633540.71       6838548.2
#Sta/Elev= 30
  4109.1 1895.28  4501.9  1887.6  4700.4 1886.65  4805.1 1885.45  4827.6 1884.68
    4850 1885.29  4861.4  1884.3  4872.6 1884.05  4873.1 1883.55  4882.8 1883.55
  4883.3 1884.05  4883.7 1884.66  4891.8 1885.64  4897.3 1885.64    4901 1888.15
  4906.3  1887.9  4916.2 1889.59  4957.2  1889.1  4969.3 1889.83  4979.9 1889.36
  5003.2 1890.16  5031.1 1888.62  5051.1 1888.22  5071.2 1889.77  5111.2 1895.11
  5131.2 1896.89  5161.2 1897.52  5246.3 1901.28  5331.3 1903.74    5437 1905.47
#Mann= 3 ,-1 , 0
  4109.1     .05       0  4872.6     .05       0  4883.3     .05       0
Bank Sta=4872.6,4883.3
XS Rating Curve= 0 ,0
Exp/Cntr=0.3,0.1

Type RM Length L Ch R = 1 ,70015   ,287,287,287
BEGIN DESCRIPTION:
Buck Creek 70014.85
END DESCRIPTION:
XS GIS Cut Line= 5
      1632232.57      6838362.25      1632677.65       6838450.7
      1632944.68      6838581.86      1633065.13      6838631.77
      1633596.85      6838635.03
#Sta/Elev= 30
  4119.3 1896.02  4142.2 1896.11  4171.1 1894.63  4324.5 1890.22  4437.8 1887.76
  4458.2 1887.97  4539.8 1886.71  4592.4 1887.12  4681.5 1885.83  4734.4 1885.77
  4748.4 1885.02  4846.8 1884.28  4892.6 1882.92  4898.8 1883.89  4904.3 1883.14
  4914.2 1883.15  4957.5 1880.48  4968.4  1880.2  4975.9 1880.83  5003.4 1880.91
  5015.5 1879.85    5016 1879.35  5025.7 1879.35  5026.2 1879.85  5060.8  1888.3
  5090.8  1890.1  5170.8 1896.77  5300.8 1901.17  5410.8 1903.71  5532.7 1904.66
#Mann= 3 ,-1 , 0
  4119.3     .05       0  5015.5     .05       0  5026.2     .05       0
Bank Sta=5015.5,5026.2
XS Rating Curve= 0 ,0
Exp/Cntr=0.3,0.1

Type RM Length L Ch R = 1 ,69728   ,285,285,285
BEGIN DESCRIPTION:
Buck Creek 69727.57
END DESCRIPTION:
XS GIS Cut Line= 3
      1632163.54      6838587.93      1632957.84      6838887.42
      1633666.15      6838853.57
#Sta/Elev= 30
  4148.2 1896.15  4171.1 1896.34  4181.8 1895.02  4304.5 1889.47  4406.3 1886.59
  4545.2 1884.45  4716.2 1883.42  4823.1 1881.31  4876.5 1882.31    4896 1882.15
  4981.3 1879.89  4997.1 1879.17  5004.3 1878.08  5018.9 1877.68  5019.4 1877.18
  5029.1 1877.18  5029.6 1877.68  5044.3 1877.81  5054.3 1879.24  5064.3 1882.42
  5074.3 1884.22  5089.5 1885.08  5094.5 1884.64  5114.4 1886.14  5174.4 1887.78
  5294.4 1889.87  5404.7 1894.01  5504.2 1895.75  5509.2 1896.59  5706.2 1897.19
#Mann= 3 ,-1 , 0
  4148.2     .05       0  5018.9     .05       0  5029.6     .05       0
Bank Sta=5018.9,5029.6
XS Rating Curve= 0 ,0
Exp/Cntr=0.3,0.1

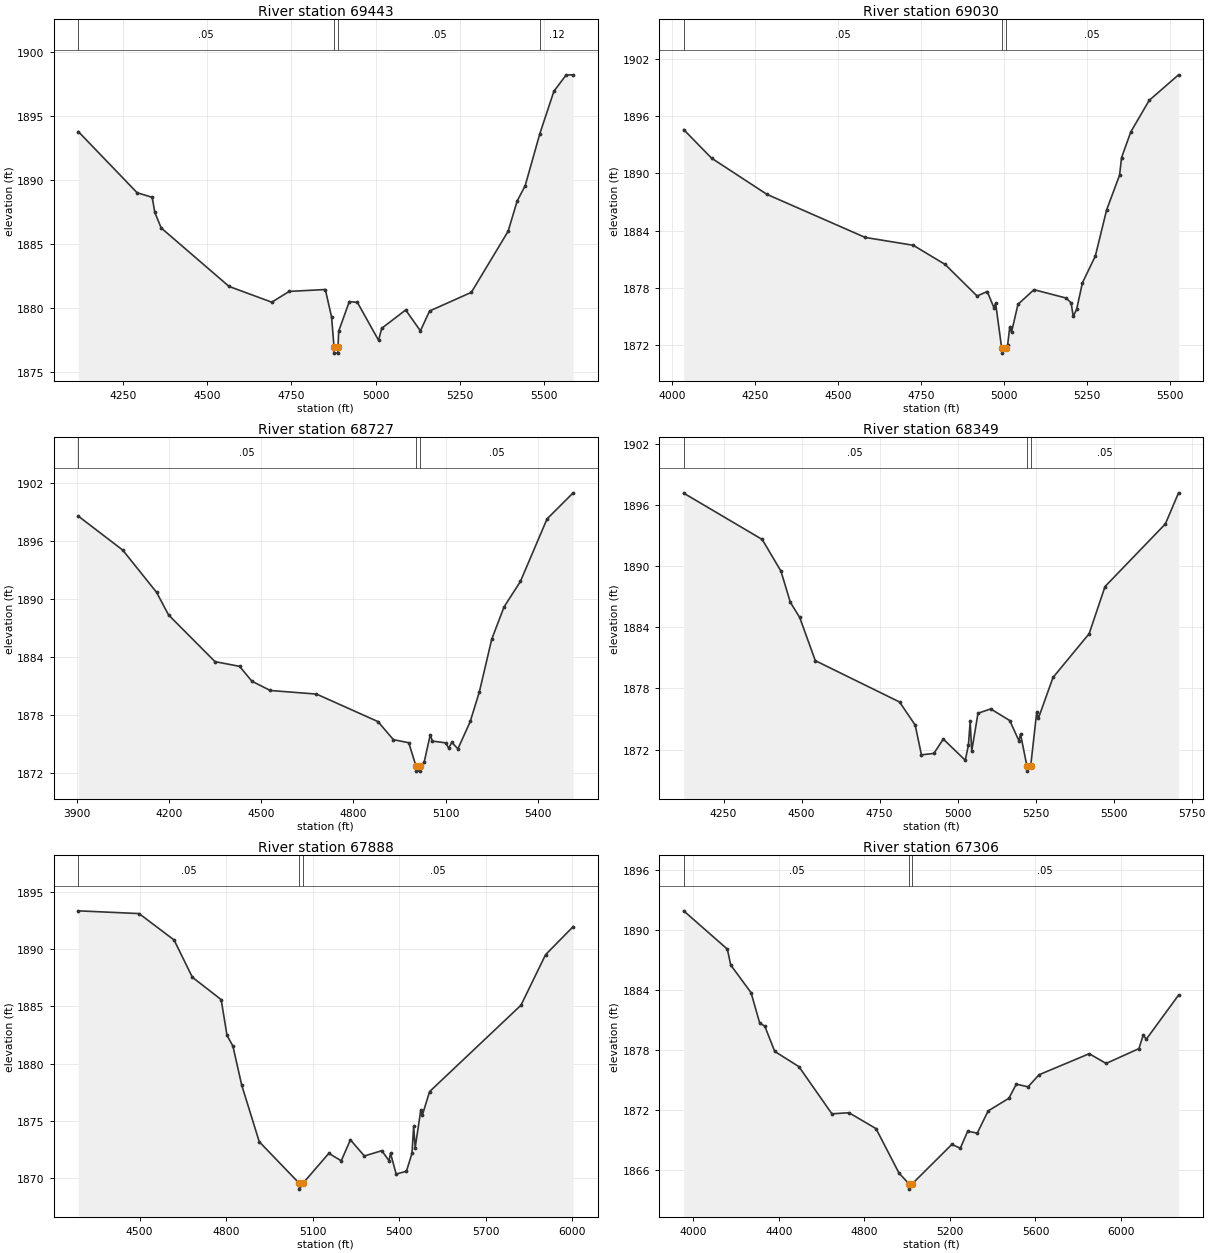
Type RM Length L Ch R = 1 ,69443   ,413,413,413
BEGIN DESCRIPTION:
Buck Creek 69443.19
END DESCRIPTION:
XS GIS Cut Line= 3
      1632008.66       6838865.3      1632850.64      6839140.89
      1633345.42      6839455.56
#Sta/Elev= 30
  4115.7 1893.79  4290.7 1889.01  4335.7 1888.65  4343.3 1887.48  4362.3 1886.26
  4564.3 1881.69  4691.4 1880.46  4743.2  1881.3  4850.7 1881.45  4869.4 1879.29
  4876.5 1876.98    4877 1876.48    4888 1876.48  4888.5 1876.98  4890.5  1878.2
  4922.1 1880.51  4946.2 1880.44  5009.1 1877.48  5018.5 1878.42  5089.8 1879.85
  5133.6 1878.22  5160.9 1879.77  5285.2 1881.23  5394.4 1885.99  5421.6 1888.37
  5445.3 1889.56  5488.9 1893.62  5530.8 1896.94  5567.2 1898.21    5588 1898.22
#Mann= 4 ,-1 , 0
  4115.7     .05       0  4876.5     .03       0  4888.5     .05       0
  5488.9     .12       0
Bank Sta=4876.5,4888.5
XS Rating Curve= 0 ,0
Exp/Cntr=0.3,0.1

Type RM Length L Ch R = 1 ,69030   ,303,303,303
BEGIN DESCRIPTION:
Buck Creek 69029.65
END DESCRIPTION:
XS GIS Cut Line= 3
      1631809.43      6839325.94      1632757.32      6839518.64
      1633259.94      6839661.87
#Sta/Elev= 30
    4035 1894.59  4118.9  1891.6  4285.6 1887.81  4581.5  1883.3  4726.2 1882.48
  4822.3 1880.47  4918.3 1877.17  4948.9 1877.64  4969.1 1875.95  4974.2 1876.41
  4992.5 1871.69    4993 1871.19  5004.6 1871.69  5010.3 1872.01  5016.8 1873.95
    5022 1873.37  5041.5  1876.3  5089.7 1877.83    5187 1876.95  5201.6 1876.44
  5207.8 1875.04  5218.2 1875.78  5235.5 1878.55  5274.5 1881.36  5308.3 1886.17
  5347.4 1889.82  5353.4 1891.66  5381.2 1894.35  5436.6 1897.65  5524.9 1900.32
#Mann= 3 ,-1 , 0
    4035     .05       0  4992.5     .05       0  5004.6     .05       0
Bank Sta=4992.5,5004.6
XS Rating Curve= 0 ,0
Exp/Cntr=0.3,0.1

Type RM Length L Ch R = 1 ,68727   ,378,378,378
BEGIN DESCRIPTION:
Buck Creek 68727.2
END DESCRIPTION:
XS GIS Cut Line= 3
      1631710.47      6839857.18       1632804.2       6839805.1
      1633319.81      6839786.87
#Sta/Elev= 30
  3904.5 1898.59  4049.2 1895.07  4159.3  1890.7  4198.5 1888.35  4349.5 1883.52
  4429.6 1883.03  4469.7 1881.49  4529.7 1880.53  4679.9 1880.16  4880.1 1877.31
  4930.2 1875.44  4980.2 1875.12  5004.2 1872.68  5004.7 1872.18  5015.8 1872.18
  5016.3 1872.68  5030.3 1873.09  5050.3 1875.94  5057.1 1875.29  5100.3 1875.11
  5110.3 1874.56  5120.3 1875.16  5140.4 1874.49  5180.4 1877.32  5210.4 1880.42
  5250.4 1885.84  5290.4 1889.18  5343.7 1891.82  5430.5  1898.3  5515.4    1901
#Mann= 3 ,-1 , 0
  3904.5     .05       0  5004.2     .05       0  5016.3     .05       0
Bank Sta=5004.2,5016.3
XS Rating Curve= 0 ,0
Exp/Cntr=0.3,0.1

Type RM Length L Ch R = 1 ,68349   ,461,461,461
BEGIN DESCRIPTION:
Buck Creek 68348.98
END DESCRIPTION:
XS GIS Cut Line= 3
      1631783.34      6840151.46      1632660.97      6840130.62
      1633356.33       6839997.8
#Sta/Elev= 30
  4122.2 1897.18  4373.9 1892.63  4433.9 1889.52    4464 1886.46    4494 1884.97
    4544 1880.73    4814 1876.67  4864.1  1874.4  4884.1 1871.48  4924.1 1871.62
  4954.1 1873.03  5024.5 1870.95  5034.7 1872.43  5040.3 1874.77  5045.3 1871.86
  5065.3 1875.56    5106 1875.99  5167.1 1874.85  5196.6 1872.86  5201.6 1873.53
  5222.1 1870.38  5222.6 1869.88  5234.2 1870.38  5253.7 1875.72  5258.8 1875.06
  5305.8 1879.08  5421.6 1883.38  5472.5 1888.01  5665.9 1894.16    5708 1897.21
#Mann= 3 ,-1 , 0
  4122.2     .05       0  5222.1     .03       0  5234.2     .05       0
Bank Sta=5222.1,5234.2
XS Rating Curve= 0 ,0
Exp/Cntr=0.3,0.1

Type RM Length L Ch R = 1 ,67888   ,582,582,582
BEGIN DESCRIPTION:
Buck Creek 67888.43
END DESCRIPTION:
XS GIS Cut Line= 3
       1631657.6      6840312.92      1632360.71      6840440.52
      1633298.17      6840088.97
#Sta/Elev= 30
  4287.1 1893.33  4497.9 1893.09  4619.2 1890.79  4682.7 1887.54  4782.5 1885.59
  4802.8 1882.47  4823.1 1881.55  4853.6 1878.15  4914.6  1873.2  5053.6 1869.57
  5054.1 1869.07  5065.8 1869.57  5155.8 1872.19  5198.9 1871.54  5230.6 1873.37
    5279 1871.96  5339.5 1872.42  5364.5 1871.55  5369.8 1872.19  5389.4 1870.38
    5425 1870.63  5444.2  1872.2  5449.9 1874.55  5455.2 1872.68  5474.8 1875.99
  5480.2 1875.53  5505.1 1877.57  5821.9  1885.1  5907.4 1889.51  6002.9 1891.95
#Mann= 3 ,-1 , 0
  4287.1     .05       0  5053.6     .03       0  5065.8     .05       0
Bank Sta=5053.6,5065.8
XS Rating Curve= 0 ,0
Exp/Cntr=0.3,0.1

Type RM Length L Ch R = 1 ,67306   ,406,406,406
BEGIN DESCRIPTION:
Buck Creek 67306.42
END DESCRIPTION:
XS GIS Cut Line= 3
      1630972.39      6841020.99      1632011.49      6840888.17
      1633234.02      6840552.63
#Sta/Elev= 30
  3954.1 1891.95  4158.4 1888.12  4174.2 1886.53  4269.3 1883.77  4309.6 1880.74
  4333.7 1880.41  4380.1 1877.89  4493.2 1876.37  4647.7 1871.65  4727.5 1871.76
    4854 1870.17  4961.7 1865.72  5009.5 1864.62    5010 1864.12  5021.9 1864.62
  5208.8 1868.59  5248.4 1868.21  5282.9 1869.91  5327.7 1869.72  5378.6 1871.94
  5475.8 1873.21  5510.3 1874.62  5565.3 1874.35  5617.1 1875.56  5851.4 1877.66
  5930.7 1876.69    6084 1878.17  6104.5 1879.54  6118.5 1879.11  6269.4 1883.52
#Mann= 3 ,-1 , 0
  3954.1     .05       0  5009.5     .05       0  5021.9     .05       0
Bank Sta=5009.5,5021.9
XS Rating Curve= 0 ,0
Exp/Cntr=0.3,0.1

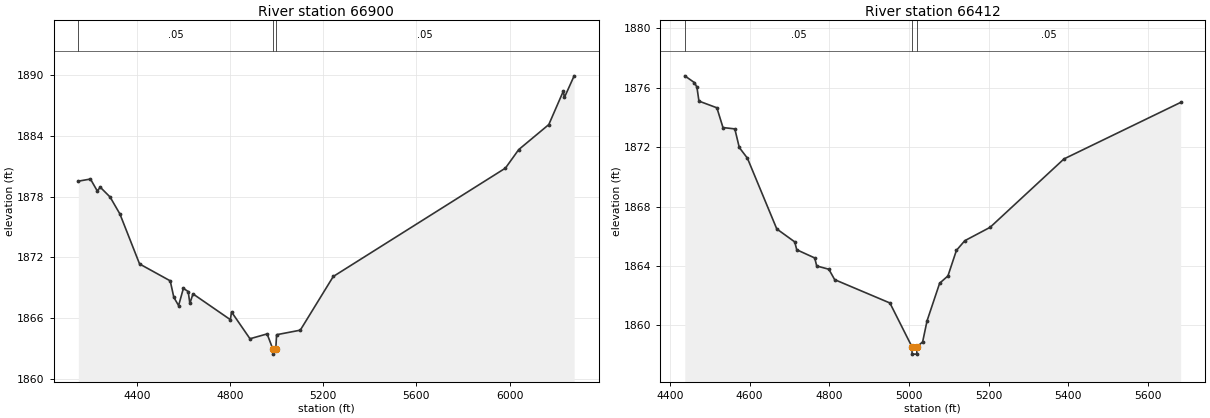
Type RM Length L Ch R = 1 ,66900   ,488,488,488
BEGIN DESCRIPTION:
Buck Creek 66900.23
END DESCRIPTION:
XS GIS Cut Line= 3
      1630995.82      6841414.23       1631829.2       6841216.3
      1633087.05      6841015.77
#Sta/Elev= 30
  4147.4 1879.54  4199.5 1879.75  4228.8 1878.57  4241.7 1878.94  4283.9 1877.97
  4326.1 1876.29  4410.5 1871.35  4542.2 1869.68  4557.7 1868.05  4578.2 1867.23
  4598.8 1868.94  4619.4 1868.62  4626.6 1867.44  4639.9 1868.39  4800.5 1865.84
  4805.7  1866.6  4884.9 1863.95  4958.5 1864.43  4983.1 1862.93  4983.6 1862.43
  4995.7 1862.93  4999.2 1864.35    5101  1864.8  5242.7 1870.11  5982.4 1880.83
  6039.4 1882.66  6168.8 1885.14  6230.9 1888.43    6236 1887.83  6277.7 1889.96
#Mann= 3 ,-1 , 0
  4147.4     .05       0  4983.1     .03       0  4995.7     .05       0
Bank Sta=4983.1,4995.7
XS Rating Curve= 0 ,0
Exp/Cntr=0.3,0.1

Type RM Length L Ch R = 1 ,66412   ,391,391,391
BEGIN DESCRIPTION:
Buck Creek 66411.94
END DESCRIPTION:
XS GIS Cut Line= 3
      1630961.21      6841466.61      1631514.63      6841581.63
       1632159.2      6841794.32
#Sta/Elev= 30
  4437.5 1876.79  4461.8 1876.33  4467.9 1876.03    4473 1875.09    4518 1874.64
  4533.3 1873.31    4563 1873.22  4574.2 1871.97  4594.6 1871.25  4668.3 1866.49
  4713.3 1865.62  4718.4 1865.09  4763.4 1864.54  4768.5    1864  4798.9 1863.78
  4813.5 1863.08  4952.1 1861.51  5007.3 1858.57  5007.8 1858.07  5019.5 1858.07
    5020 1858.57  5034.2 1858.89  5045.3 1860.31  5076.9 1862.84  5097.7 1863.33
    5119 1865.05    5140  1865.7  5203.5  1866.6  5388.8  1871.2  5681.5    1875
#Mann= 3 ,-1 , 0
  4437.5     .05       0  5007.3     .05       0    5020     .05       0
Bank Sta=5007.3,5020
XS Rating Curve= 0 ,0
Exp/Cntr=0.3,0.1