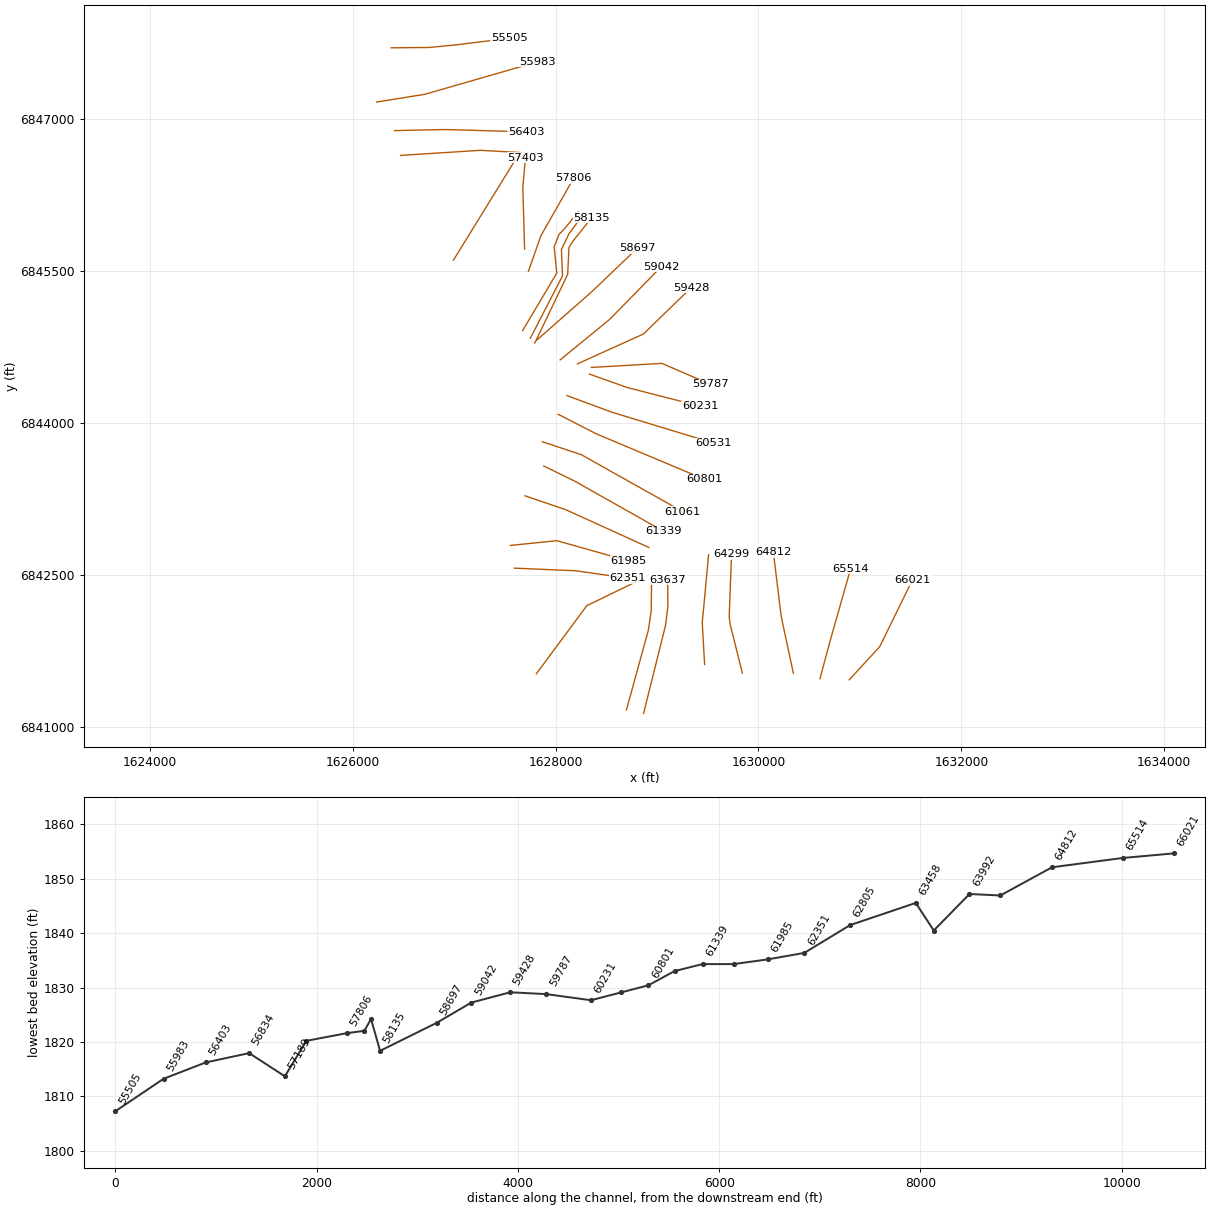
HEC-RAS study Buck Creek.prj: Buck Creek Base Level Engineering

--- Buck Creek.g01 (geometry) --- (continued)

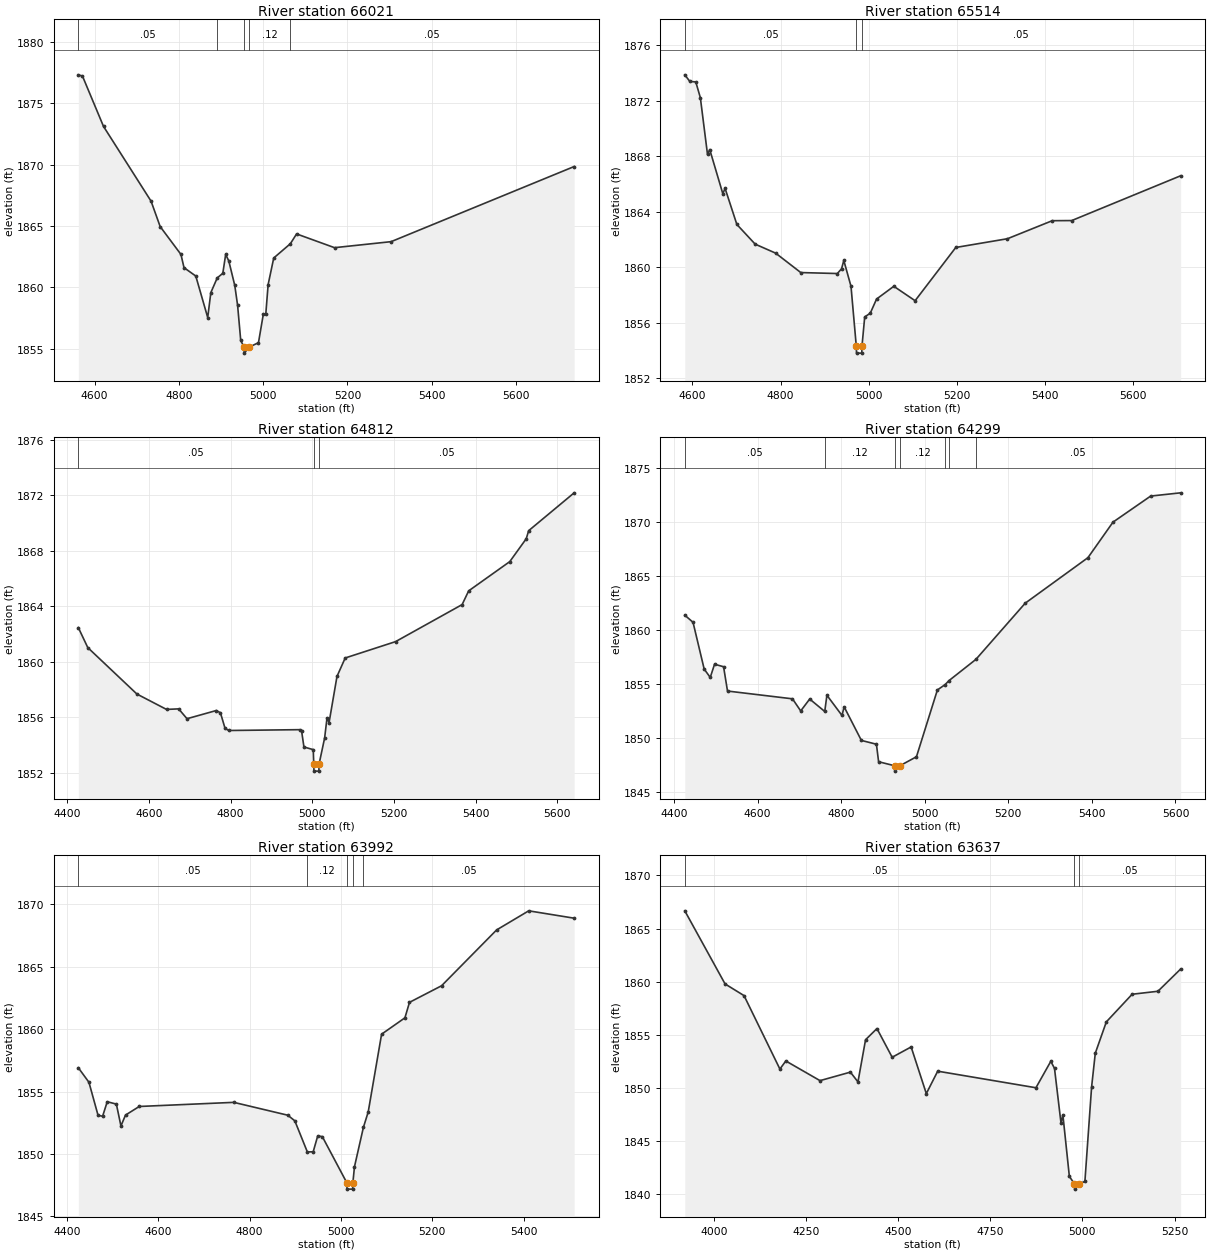
Type RM Length L Ch R = 1 ,66021   ,507,507,507
BEGIN DESCRIPTION:
Buck Creek 66020.61
END DESCRIPTION:
XS GIS Cut Line= 3
      1630895.49      6841463.51        1631195.      6841789.06
      1631517.92      6842447.91
#Sta/Elev= 30
  4561.6 1877.32  4571.4 1877.22  4621.3 1873.12  4734.1 1867.03  4755.7 1864.96
    4805 1862.69  4812.3 1861.61  4840.2 1860.93  4868.5 1857.55  4875.9 1859.58
  4891.1 1860.78  4904.3 1861.15  4911.1 1862.69  4918.5 1862.16  4932.7 1860.16
  4939.4 1858.54  4946.8 1855.68  4954.6 1855.15  4955.1 1854.65  4967.4 1855.15
  4988.9  1855.5  5000.3  1857.8  5006.2  1857.8  5011.8 1860.23  5025.1  1862.4
  5064.5 1863.56  5079.3 1864.36  5169.3 1863.24  5303.5 1863.73  5737.7 1869.85
#Mann= 5 ,-1 , 0
  4561.6     .05       0  4891.1     .12       0  4954.6     .07       0
  4967.4     .12       0  5064.5     .05       0
Bank Sta=4954.6,4967.4
XS Rating Curve= 0 ,0
Exp/Cntr=0.3,0.1

Type RM Length L Ch R = 1 ,65514   ,702,702,702
BEGIN DESCRIPTION:
Buck Creek 65514.36
END DESCRIPTION:
XS GIS Cut Line= 3
      1630606.45      6841473.93      1630715.84      6841880.21
      1630908.54      6842557.28
#Sta/Elev= 30
  4582.8 1873.88  4594.3  1873.4  4607.7 1873.37  4618.1 1872.23  4634.3 1868.14
  4639.4 1868.49    4669 1865.31  4674.2 1865.69  4700.9 1863.09  4742.4 1861.67
  4788.9 1861.02  4845.9 1859.62  4928.8 1859.55  4938.3 1859.89  4943.5 1860.49
  4959.8 1858.63  4971.8 1854.31  4972.3 1853.81  4984.2 1853.81  4984.7 1854.31
  4990.9 1856.42  5003.5 1856.69  5017.8 1857.71  5056.9 1858.63  5105.2 1857.59
  5197.5 1861.43  5314.7 1862.06  5416.3 1863.36  5460.5 1863.37  5707.5  1866.6
#Mann= 3 ,-1 , 0
  4582.8     .05       0  4971.8     .03       0  4984.7     .05       0
Bank Sta=4971.8,4984.7
XS Rating Curve= 0 ,0
Exp/Cntr=0.3,0.1

Type RM Length L Ch R = 1 ,64812   ,513,513,513
BEGIN DESCRIPTION:
Buck Creek 64811.98
END DESCRIPTION:
XS GIS Cut Line= 3
       1630344.3      6841527.82      1630224.52      6842087.67
      1630146.55      6842724.39
#Sta/Elev= 30
  4427.4 1862.45  4450.5 1861.01  4570.8 1857.66  4643.3 1856.55    4673 1856.59
  4693.5 1855.88  4765.1 1856.47  4775.3 1856.31  4786.6 1855.19  4795.7 1855.03
  4969.1 1855.09  4974.2 1854.96  4979.8 1853.84  5002.6 1853.65  5003.8  1852.6
  5004.3  1852.1  5016.3  1852.1  5016.8  1852.6  5030.5  1854.5  5036.3 1855.94
  5041.3  1855.6  5060.7 1858.93  5080.8 1860.26  5204.2 1861.44  5367.1 1864.11
  5383.1  1865.1  5483.8 1867.21  5524.1 1868.86    5530 1869.44  5641.4 1872.17
#Mann= 3 ,-1 , 0
  4427.4     .05       0  5003.8     .05       0  5016.8     .05       0
Bank Sta=5003.8,5016.8
XS Rating Curve= 0 ,0
Exp/Cntr=0.3,0.1

Type RM Length L Ch R = 1 ,64299   ,307,307,307
BEGIN DESCRIPTION:
Buck Creek 64298.97
END DESCRIPTION:
XS GIS Cut Line= 4
       1629841.5      6841528.88      1629721.91      6842006.95
       1629711.5      6842087.67      1629734.93      6842699.63
#Sta/Elev= 30
  4425.8 1861.35  4445.5 1860.69  4472.2 1856.36  4486.7 1855.59    4497 1856.81
  4518.6 1856.58    4528 1854.33  4683.5 1853.61  4703.2 1852.49  4724.7 1853.59
  4760.7 1852.44  4765.9 1853.94    4802 1852.07  4807.1 1852.87  4848.4 1849.76
  4884.4 1849.41  4889.6 1847.79  4927.7 1847.42  4928.2 1846.92  4940.7 1847.42
  4980.2 1848.25  5030.3 1854.43  5048.9 1854.93  5058.2  1855.3  5122.5 1857.26
  5240.5 1862.46  5390.6 1866.67  5450.6 1869.96  5540.7 1872.37  5612.4 1872.67
#Mann= 7 ,-1 , 0
  4425.8     .05       0  4760.7     .12       0  4927.7     .07       0
  4940.7     .12       0  5048.9     .05       0  5058.2     .12       0
  5122.5     .05       0
Bank Sta=4927.7,4940.7
XS Rating Curve= 0 ,0
Exp/Cntr=0.3,0.1

Type RM Length L Ch R = 1 ,63992   ,355,355,355
BEGIN DESCRIPTION:
Buck Creek 63992.1
END DESCRIPTION:
XS GIS Cut Line= 4
       1629469.1      6841614.84      1629445.87      6842030.38
       1629461.5      6842189.24      1629508.37      6842697.07
#Sta/Elev= 30
    4425 1856.91  4448.2 1855.75  4468.2  1853.1  4478.2 1853.03  4488.3 1854.19
  4508.3    1854  4518.3 1852.25  4528.3 1853.12  4558.4 1853.81  4765.4 1854.14
  4883.7 1853.11  4899.1 1852.66  4926.5 1850.17  4939.3 1850.18  4949.3 1851.46
  4959.4 1851.39  5013.1 1847.69  5013.6 1847.19  5025.7 1847.19  5026.2 1847.69
  5029.7 1848.98  5049.3 1852.14  5059.8 1853.37  5089.1  1859.6  5140.2 1860.91
  5150.2 1862.15  5220.5 1863.48    5341 1867.95  5411.3 1869.48  5510.8 1868.89
#Mann= 5 ,-1 , 0
    4425     .05       0  4926.5     .12       0  5013.1     .07       0
  5026.2     .12       0  5049.3     .05       0
Bank Sta=5013.1,5026.2
XS Rating Curve= 0 ,0
Exp/Cntr=0.3,0.1

Type RM Length L Ch R = 1 ,63637   ,179,179,179
BEGIN DESCRIPTION:
Buck Creek 63637.04
END DESCRIPTION:
XS GIS Cut Line= 4
      1628867.74      6841131.94      1629083.89      6841999.13
      1629107.33      6842186.63      1629104.73      6842449.64
#Sta/Elev= 30
  3920.8 1866.67  4030.1 1859.79  4081.6 1858.69  4178.9 1851.78    4195 1852.54
  4287.8 1850.69  4370.2 1851.49  4390.8 1850.57  4411.4 1854.54  4442.3 1855.59
  4483.6 1852.89  4535.1 1853.86  4576.3 1849.47  4607.2 1851.58  4873.8 1850.02
  4914.2 1852.51  4924.2 1851.84  4941.9 1846.68  4946.9 1847.48  4964.5 1841.68
  4978.2 1840.98  4978.7 1840.48  4991.3 1840.98  5006.7  1841.2  5024.9  1850.1
  5034.9 1853.27  5064.9 1856.22  5134.9 1858.82  5204.9  1859.1  5266.5 1861.19
#Mann= 3 ,-1 , 0
  3920.8     .05       0  4978.2     .03       0  4991.3     .05       0
Bank Sta=4978.2,4991.3
XS Rating Curve= 0 ,0
Exp/Cntr=0.3,0.1

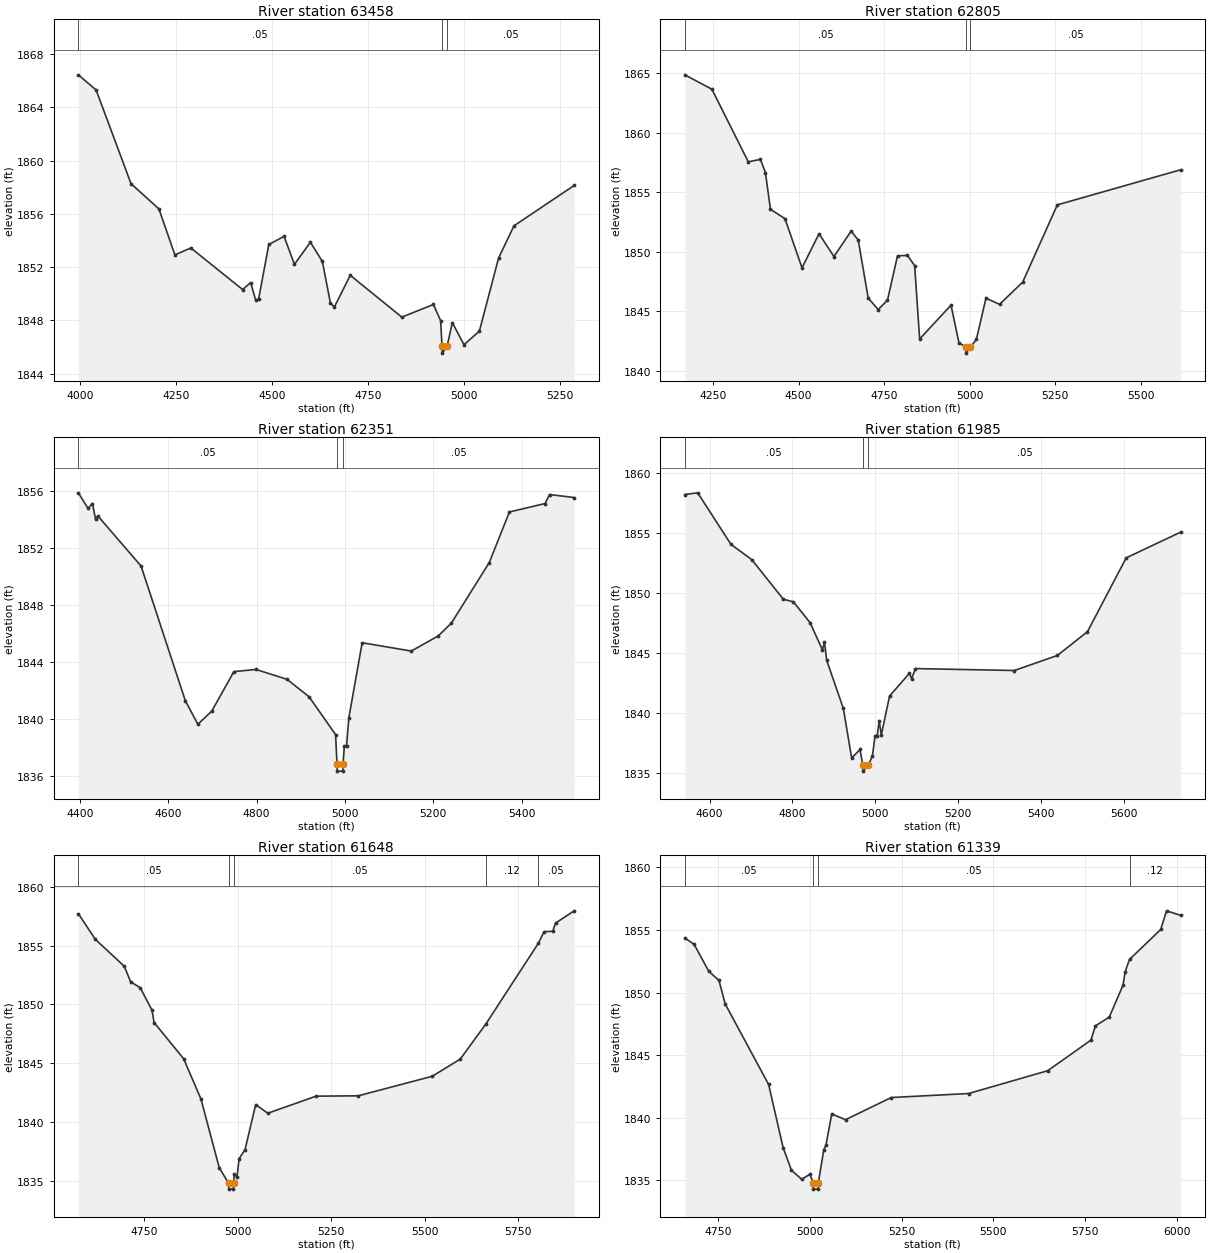
Type RM Length L Ch R = 1 ,63458   ,653,653,653
BEGIN DESCRIPTION:
Buck Creek 63457.53
END DESCRIPTION:
XS GIS Cut Line= 4
      1628698.46      6841165.76      1628914.62      6841952.26
      1628943.27      6842144.97      1628945.86      6842424.57
#Sta/Elev= 30
  3996.1 1866.43  4042.4 1865.29  4133.2 1858.26  4205.8 1856.37  4247.3 1852.92
  4288.8 1853.44  4423.6 1850.32  4444.4 1850.84  4457.3 1849.55  4465.1 1849.59
  4491.7  1853.7  4531.4 1854.31  4558.4 1852.21  4599.9 1853.87    4631 1852.43
  4651.8 1849.34  4662.2    1849  4703.6 1851.39  4837.8 1848.25    4920  1849.2
  4938.9 1847.98  4942.4 1846.05  4942.9 1845.55  4955.5 1846.05  4969.2 1847.84
  4999.5 1846.18  5039.6  1847.2  5089.6 1852.69  5129.6  1855.1  5286.2 1858.13
#Mann= 3 ,-1 , 0
  3996.1     .05       0  4942.4     .03       0  4955.5     .05       0
Bank Sta=4942.4,4955.5
XS Rating Curve= 0 ,0
Exp/Cntr=0.3,0.1

Type RM Length L Ch R = 1 ,62805   ,454,454,454
BEGIN DESCRIPTION:
Buck Creek 62805.2
END DESCRIPTION:
XS GIS Cut Line= 3
      1627810.46      6841522.57      1628307.85      6842194.45
      1628859.89      6842462.66
#Sta/Elev= 30
  4167.2 1864.86  4246.4 1863.65  4352.8 1857.55  4388.3 1857.75  4402.9 1856.65
  4417.6 1853.56  4460.1 1852.77  4509.9 1848.64  4559.7  1851.5  4603.3 1849.59
  4653.4 1851.72  4674.2 1850.98  4703.5  1846.1  4732.7 1845.13  4759.8 1845.92
  4789.1 1849.65  4818.3 1849.68  4839.2 1848.83  4853.8 1842.66  4945.6  1845.5
  4968.6 1842.35  4988.9 1841.97  4989.4 1841.47  5002.4 1841.97  5019.7 1842.62
  5047.8 1846.09  5087.4 1845.57    5155 1847.43  5256.4 1853.93  5616.9 1856.88
#Mann= 3 ,-1 , 0
  4167.2     .05       0  4988.9     .03       0  5002.4     .05       0
Bank Sta=4988.9,5002.4
XS Rating Curve= 0 ,0
Exp/Cntr=0.3,0.1

Type RM Length L Ch R = 1 ,62351   ,366,366,366
BEGIN DESCRIPTION:
Buck Creek 62351.01
END DESCRIPTION:
XS GIS Cut Line= 3
      1627592.98      6842564.76      1628199.78      6842538.72
      1628710.14      6842465.81
#Sta/Elev= 30
  4396.1 1855.86  4418.1 1854.77  4428.1 1855.11  4435.1 1854.01  4440.1 1854.25
  4538.2 1850.73  4638.3 1841.31  4666.8 1839.65  4698.4 1840.58  4748.4 1843.34
  4798.5 1843.49  4868.6  1842.8  4918.6 1841.58  4978.7 1838.93  4981.9 1836.87
  4982.4 1836.37    4995 1836.37  4995.5 1836.87  4998.6 1838.13  5003.5 1838.13
  5008.7  1840.1  5038.9 1845.36  5150.1 1844.78  5210.8 1845.83  5241.1 1846.74
  5326.8 1850.98  5372.4 1854.52  5453.2 1855.11  5463.2 1855.74    5519 1855.53
#Mann= 3 ,-1 , 0
  4396.1     .05       0  4981.9     .05       0  4995.5     .05       0
Bank Sta=4981.9,4995.5
XS Rating Curve= 0 ,0
Exp/Cntr=0.3,0.1

Type RM Length L Ch R = 1 ,61985   ,337,337,337
BEGIN DESCRIPTION:
Buck Creek 61984.8
END DESCRIPTION:
XS GIS Cut Line= 3
      1627553.96      6842788.72      1628012.28      6842835.59
      1628721.59      6842635.53
#Sta/Elev= 30
  4540.1 1858.18  4571.3 1858.32  4651.7 1854.03    4702 1852.76  4778.1 1849.47
  4802.5 1849.25  4842.7 1847.52  4872.5 1845.26  4877.5  1845.9  4882.9 1844.38
  4923.1 1840.38  4943.2 1836.26  4963.3 1836.97  4970.1 1835.67  4970.6 1835.17
  4983.7 1835.67  4993.5 1836.46  4999.7 1838.11  5004.8 1838.11  5009.6 1839.34
  5014.8 1838.19  5034.8 1841.42  5082.8 1843.31    5088 1842.86  5097.2  1843.7
  5336.1 1843.54    5440 1844.79  5512.8 1846.77  5606.3 1852.91  5737.8 1855.05
#Mann= 3 ,-1 , 0
  4540.1     .05       0  4970.1     .05       0  4983.7     .05       0
Bank Sta=4970.1,4983.7
XS Rating Curve= 0 ,0
Exp/Cntr=0.3,0.1

Type RM Length L Ch R = 1 ,61648   ,309,309,309
BEGIN DESCRIPTION:
Buck Creek 61647.98
END DESCRIPTION:
XS GIS Cut Line= 3
      1627698.52      6843278.29      1628099.95      6843141.58
      1628920.16      6842768.37
#Sta/Elev= 30
  4574.3 1857.72  4619.9 1855.53  4697.4 1853.24    4714 1851.93  4739.6 1851.43
  4771.3 1849.51  4776.7 1848.47  4855.8 1845.39  4902.1 1841.96  4950.9 1836.13
  4975.8 1834.81  4976.3 1834.31  4988.9 1834.31  4989.4 1834.81  4990.9 1835.56
  4998.4 1835.32  5003.9  1836.9  5019.7 1837.65  5048.3 1841.49  5080.8 1840.76
  5209.7 1842.21  5322.5 1842.24  5520.3  1843.9  5595.1 1845.36  5663.4 1848.34
    5804 1855.21  5819.1 1856.19  5842.2 1856.22  5849.9 1856.92  5899.5 1857.96
#Mann= 5 ,-1 , 0
  4574.3     .05       0  4975.8     .05       0  4989.4     .05       0
  5663.4     .12       0    5804     .05       0
Bank Sta=4975.8,4989.4
XS Rating Curve= 0 ,0
Exp/Cntr=0.3,0.1

Type RM Length L Ch R = 1 ,61339   ,278,278,278
BEGIN DESCRIPTION:
Buck Creek 61339.01
END DESCRIPTION:
XS GIS Cut Line= 3
      1627883.42      6843572.31      1628188.96      6843423.01
      1629067.48      6842926.46
#Sta/Elev= 30
  4660.3 1854.35  4685.7 1853.85  4725.2 1851.71  4753.3 1850.96  4770.2 1849.09
  4888.4 1842.66  4927.8 1837.63  4950.4 1835.82  4978.4  1835.1  5000.4 1835.49
    5010 1834.81  5010.5 1834.31  5023.2 1834.31  5023.7 1834.81  5038.5 1837.46
  5044.3 1837.81  5060.2 1840.31  5097.7 1839.85  5221.9 1841.62  5432.6 1841.94
  5647.8 1843.76  5765.4  1846.2  5777.7 1847.34  5815.2 1848.03  5852.8 1850.59
  5858.5 1851.66  5870.4 1852.64  5955.3 1855.03  5971.2 1856.52  6009.5 1856.16
#Mann= 4 ,-1 , 0
  4660.3     .05       0    5010     .05       0  5023.7     .05       0
  5870.4     .12       0
Bank Sta=5010,5023.7
XS Rating Curve= 0 ,0
Exp/Cntr=0.3,0.1

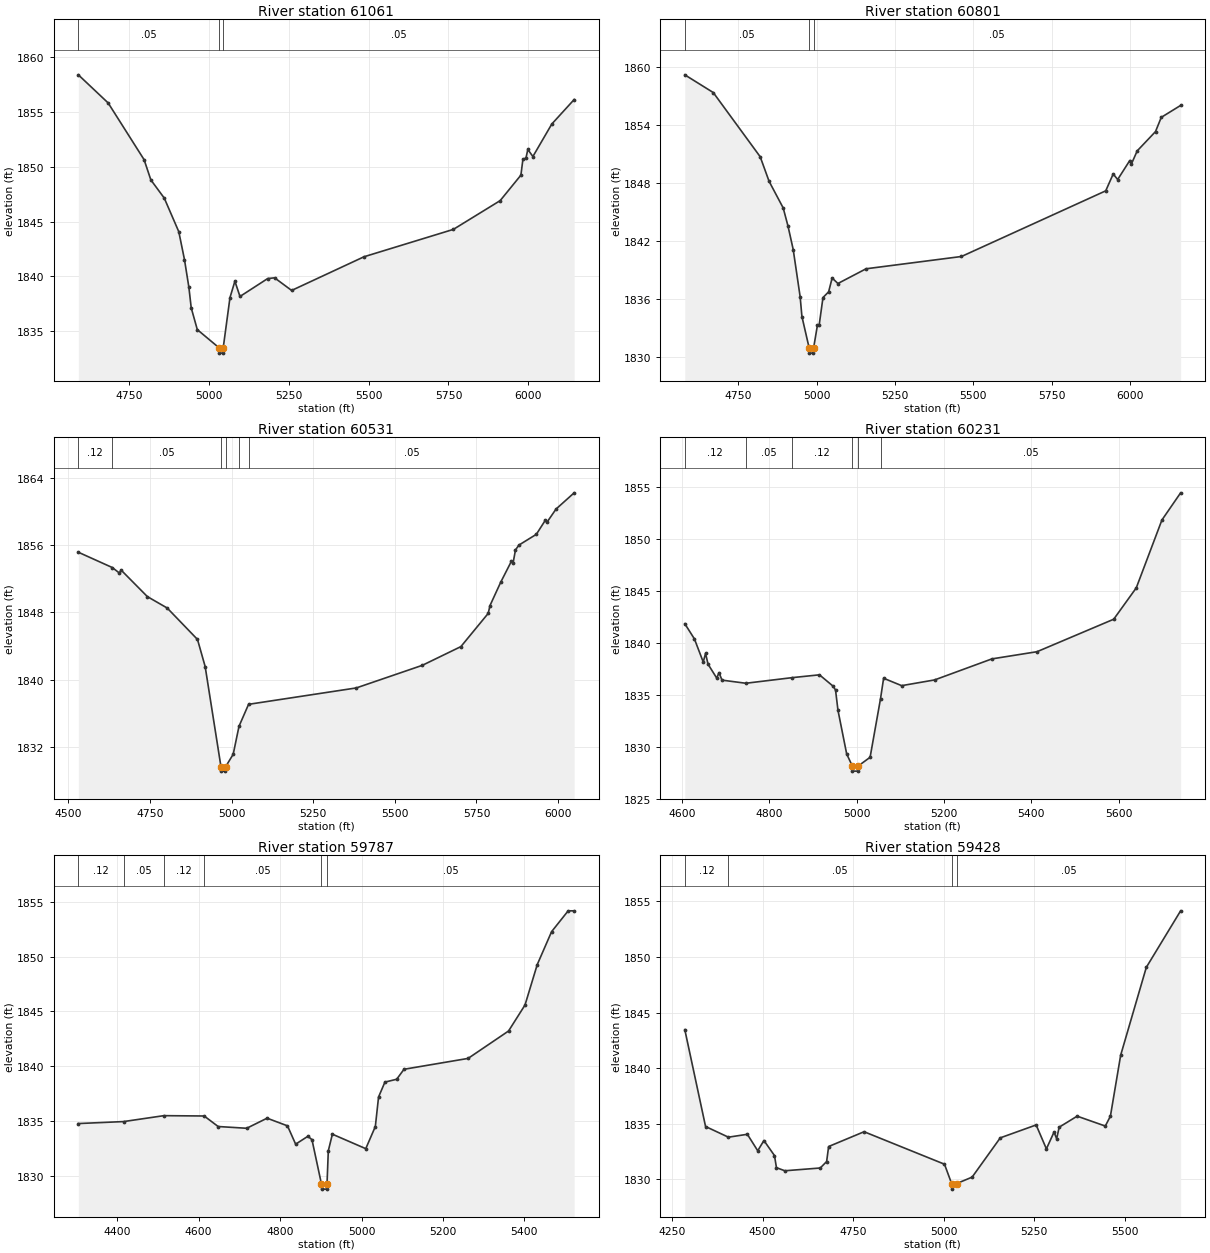
Type RM Length L Ch R = 1 ,61061   ,260,260,260
BEGIN DESCRIPTION:
Buck Creek 61060.69
END DESCRIPTION:
XS GIS Cut Line= 3
      1627869.48      6843811.91      1628254.93      6843683.43
      1629254.97      6843120.91
#Sta/Elev= 30
  4590.1 1858.37  4683.5 1855.81  4796.2 1850.64  4817.3  1848.8  4859.4 1847.14
  4904.9 1844.08  4922.7 1841.54  4936.5 1839.02  4943.8 1837.15  4962.9 1835.16
  5030.5 1833.52    5031 1833.02  5043.7 1833.02  5044.2 1833.52  5065.3 1838.08
  5080.7 1839.57  5096.6 1838.18  5183.3 1839.81    5205 1839.88  5258.5 1838.73
  5485.5  1841.8  5765.2 1844.29  5911.9 1846.91  5976.9 1849.23  5983.2 1850.67
  5992.8 1850.79  5998.6 1851.57  6014.5 1850.93  6073.8 1853.89  6143.8 1856.12
#Mann= 3 ,-1 , 0
  4590.1     .05       0  5030.5     .05       0  5044.2     .05       0
Bank Sta=5030.5,5044.2
XS Rating Curve= 0 ,0
Exp/Cntr=0.3,0.1

Type RM Length L Ch R = 1 ,60801   ,270,270,270
BEGIN DESCRIPTION:
Buck Creek 60801.45
END DESCRIPTION:
XS GIS Cut Line= 3
      1628025.79      6844082.72      1628404.24      6843888.29
       1629470.1      6843440.42
#Sta/Elev= 30
  4579.3 1859.15  4670.1 1857.32  4819.8 1850.69  4848.2 1848.15  4893.2  1845.4
  4908.5 1843.53  4925.1 1841.11  4947.2 1836.24  4952.9 1834.19  4976.2 1830.91
  4976.7 1830.41  4989.5 1830.41    4990 1830.91  5002.4  1833.3  5007.9  1833.3
  5020.1 1836.15  5038.1 1836.74  5049.3 1838.17  5067.7  1837.6  5157.5 1839.12
  5461.9 1840.39    5922 1847.17  5945.8 1848.91  5960.1 1848.34  5998.7  1850.3
  6004.1 1849.96  6022.5  1851.3  6080.8 1853.29  6099.2 1854.76  6160.9 1855.99
#Mann= 3 ,-1 , 0
  4579.3     .05       0  4976.2     .05       0    4990     .05       0
Bank Sta=4976.2,4990
XS Rating Curve= 0 ,0
Exp/Cntr=0.3,0.1

Type RM Length L Ch R = 1 ,60531   ,300,300,300
BEGIN DESCRIPTION:
Buck Creek 60530.9
END DESCRIPTION:
XS GIS Cut Line= 3
      1628112.59      6844266.76      1628553.55      6844103.57
      1629556.98      6843798.02
#Sta/Elev= 30
  4530.2 1855.16  4634.2 1853.34  4655.8 1852.69  4661.2 1853.04  4741.7 1849.88
  4802.5 1848.52  4895.3 1844.78  4918.8 1841.55  4967.3 1829.61  4967.8 1829.11
  4980.6 1829.11  4981.1 1829.61  5004.7 1831.12  5022.5 1834.45  5051.8 1837.06
  5381.7 1839.01    5584  1841.7  5702.3 1843.93  5785.9 1847.88  5791.5 1848.82
  5824.4  1851.6  5857.2  1854.1  5862.4 1853.92  5869.5 1855.43    5880 1856.01
  5933.4 1857.29    5961 1858.97  5966.2 1858.74  5993.8  1860.3  6049.3 1862.23
#Mann= 6 ,-1 , 0
  4530.2     .12       0  4634.2     .05       0  4967.3     .05       0
  4981.1     .05       0  5022.5     .12       0  5051.8     .05       0
Bank Sta=4967.3,4981.1
XS Rating Curve= 0 ,0
Exp/Cntr=0.3,0.1

Type RM Length L Ch R = 1 ,60231   ,444,444,444
BEGIN DESCRIPTION:
Buck Creek 60230.62
END DESCRIPTION:
XS GIS Cut Line= 3
      1628334.86      6844478.82      1628704.62      6844346.88
      1629423.34      6844162.86
#Sta/Elev= 30
  4607.1 1841.83  4629.1 1840.37  4649.3 1838.15  4654.6 1838.98  4660.3 1837.94
  4680.1 1836.61  4685.4 1837.13  4692.2 1836.41  4746.8 1836.11  4852.9 1836.65
  4915.2 1836.92  4946.7 1835.82    4952 1835.46  4957.6 1833.51  4977.5 1829.32
  4990.3 1828.17  4990.8 1827.67  5003.6 1827.67  5004.1 1828.17  5031.1    1829
  5054.9 1834.62    5062 1836.59  5103.3 1835.88  5178.7 1836.43  5309.8 1838.45
    5413 1839.14  5588.5 1842.26  5640.1 1845.27  5698.8 1851.79  5741.6  1854.4
#Mann= 6 ,-1 , 0
  4607.1     .12       0  4746.8     .05       0  4852.9     .12       0
  4990.3     .07       0  5004.1     .12       0  5054.9     .05       0
Bank Sta=4990.3,5004.1
XS Rating Curve= 0 ,0
Exp/Cntr=0.3,0.1

Type RM Length L Ch R = 1 ,59787   ,359,359,359
BEGIN DESCRIPTION:
Buck Creek 59787.38
END DESCRIPTION:
XS GIS Cut Line= 3
      1628352.24       6844544.8      1629048.37      6844584.73
      1629525.81      6844378.13
#Sta/Elev= 30
  4304.6 1834.77  4415.6 1834.95  4514.6 1835.49  4613.6 1835.46  4647.9  1834.5
    4718 1834.34  4768.1 1835.26  4818.2 1834.56  4838.2 1832.89  4868.3 1833.61
  4878.3  1833.3  4901.4 1829.29  4901.9 1828.79  4914.8 1828.79  4915.3 1829.29
  4918.4 1832.28  4928.4  1833.8  5010.4 1832.48  5033.9  1834.5  5041.8 1837.19
  5057.4 1838.55  5086.3 1838.81  5104.3 1839.72  5261.6 1840.71    5361 1843.21
  5401.4 1845.58  5431.5 1849.27  5466.7 1852.27  5507.4 1854.17  5522.1 1854.17
#Mann= 6 ,-1 , 0
  4304.6     .12       0  4415.6     .05       0  4514.6     .12       0
  4613.6     .05       0  4901.4     .05       0  4915.3     .05       0
Bank Sta=4901.4,4915.3
XS Rating Curve= 0 ,0
Exp/Cntr=0.3,0.1

Type RM Length L Ch R = 1 ,59428   ,386,386,386
BEGIN DESCRIPTION:
Buck Creek 59427.6
END DESCRIPTION:
XS GIS Cut Line= 3
      1628216.08      6844580.14      1628867.09      6844875.27
      1629335.87      6845331.03
#Sta/Elev= 30
  4285.4 1843.47  4342.7 1834.76  4405.8  1833.8  4458.1 1834.06  4486.7 1832.58
  4503.8  1833.5  4532.9 1832.15  4538.4 1831.06  4561.5 1830.78  4659.3 1831.03
  4676.9 1831.61  4682.4 1832.96  4780.3 1834.29  5002.2 1831.37  5021.9 1829.63
  5022.4 1829.13  5035.8 1829.63  5078.5 1830.21  5156.2 1833.74  5255.2  1834.9
  5283.5 1832.75  5304.6 1834.26  5311.8 1833.66  5318.8  1834.7  5368.4 1835.69
  5446.1  1834.8  5460.2 1835.69  5488.5 1841.17  5559.3 1849.07    5654 1854.15
#Mann= 4 ,-1 , 0
  4285.4     .12       0  4405.8     .05       0  5021.9     .05       0
  5035.8     .05       0
Bank Sta=5021.9,5035.8
XS Rating Curve= 0 ,0
Exp/Cntr=0.3,0.1

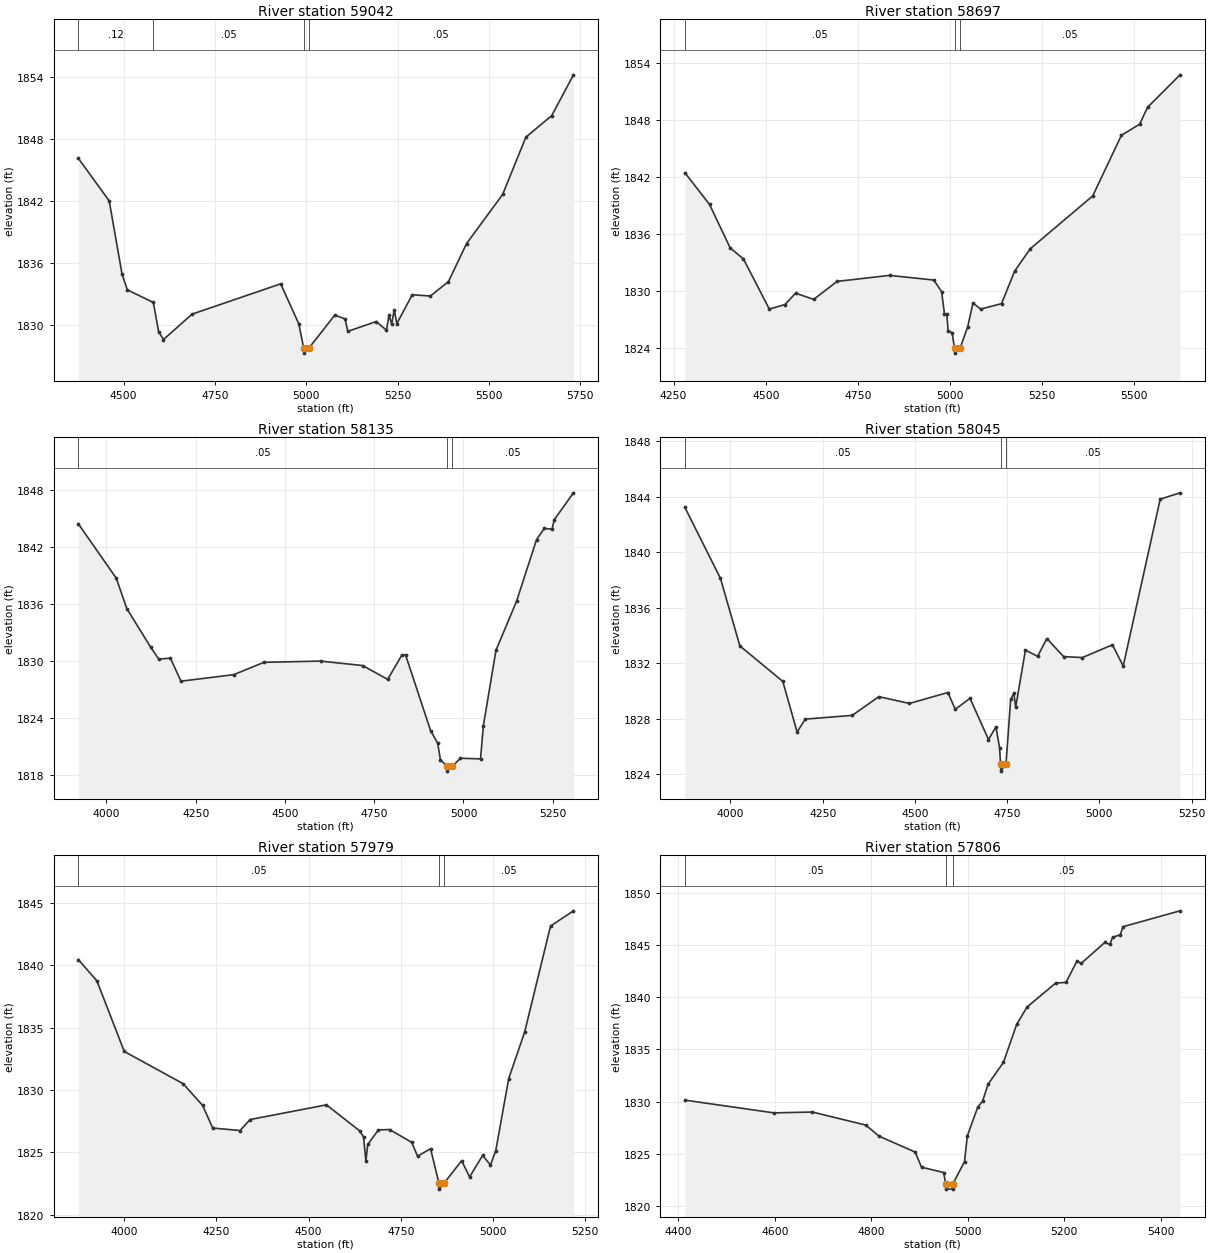
Type RM Length L Ch R = 1 ,59042   ,345,345,345
BEGIN DESCRIPTION:
Buck Creek 59041.59
END DESCRIPTION:
XS GIS Cut Line= 3
      1628044.63      6844619.21      1628530.72      6845016.33
      1629040.34      6845536.79
#Sta/Elev= 30
  4375.7 1846.14  4460.4    1842  4495.6 1834.89  4509.9 1833.38  4581.3 1832.15
  4595.7 1829.32    4609 1828.56  4687.3 1831.02  4929.9 1833.96  4979.5 1830.09
    4993 1827.74  4993.5 1827.24  5007.6 1827.74  5078.3 1830.93  5106.5 1830.55
  5113.7 1829.35  5191.4  1830.3  5219.7 1829.47  5226.8 1830.93  5233.8 1830.07
    5241 1831.44    5248  1830.1  5290.4  1832.9    5340 1832.78  5389.4 1834.17
    5439 1837.86  5537.9 1842.63  5601.6 1848.19  5672.3 1850.27  5731.8 1854.23
#Mann= 4 ,-1 , 0
  4375.7     .12       0  4581.3     .05       0    4993     .03       0
  5007.6     .05       0
Bank Sta=4993,5007.6
XS Rating Curve= 0 ,0
Exp/Cntr=0.3,0.1

Type RM Length L Ch R = 1 ,58697   ,562,562,562
BEGIN DESCRIPTION:
Buck Creek 58696.96
END DESCRIPTION:
XS GIS Cut Line= 3
       1627814.6      6844814.53      1628352.77       6845287.6
      1628806.33      6845721.62
#Sta/Elev= 30
  4280.6 1842.47  4347.5 1839.14  4403.5 1834.57  4439.6 1833.41  4509.8 1828.14
  4552.5 1828.62    4581 1829.81  4630.3 1829.16  4693.9 1831.05  4836.2 1831.68
  4956.7 1831.19  4977.6 1829.96  4985.2 1827.67  4991.8  1827.6  4995.3 1825.84
    5006 1825.67  5012.8 1824.01  5013.3 1823.51  5027.5 1824.01  5048.5 1826.29
  5062.7 1828.77  5083.7 1828.14  5140.3 1828.71  5175.9 1832.13  5218.3 1834.48
  5387.8 1840.03  5465.8 1846.41  5515.2 1847.57  5536.6 1849.34  5624.9 1852.76
#Mann= 3 ,-1 , 0
  4280.6     .05       0  5012.8     .03       0  5027.5     .05       0
Bank Sta=5012.8,5027.5
XS Rating Curve= 0 ,0
Exp/Cntr=0.3,0.1

Type RM Length L Ch R = 1 ,58135   ,90,90,90
BEGIN DESCRIPTION:
Buck Creek 58134.66
END DESCRIPTION:
XS GIS Cut Line= 5
      1627794.92      6844785.44      1628119.28       6845462.5
      1628131.91      6845727.67      1628164.46      6845782.36
      1628355.86      6846021.93
#Sta/Elev= 30
  3921.4 1844.45  4027.7 1838.71  4057.3  1835.5  4123.8 1831.45  4146.5 1830.18
  4179.3 1830.28  4208.9 1827.85  4356.7 1828.54  4441.1 1829.84  4599.7 1829.97
  4717.7  1829.5  4787.8 1828.04  4827.8 1830.63  4837.8 1830.62  4907.9 1822.64
  4927.9  1821.3  4935.3 1819.58  4953.9 1818.87  4954.4 1818.37  4968.6 1818.87
  4991.5 1819.73  5047.7 1819.66  5055.7 1823.16    5091 1831.11  5148.6 1836.28
  5204.6 1842.78  5226.1 1843.95  5247.9 1843.89  5254.3 1844.88  5307.9 1847.71
#Mann= 3 ,-1 , 0
  3921.4     .05       0  4953.9     .05       0  4968.6     .05       0
Bank Sta=4953.9,4968.6
XS Rating Curve= 0 ,0
Exp/Cntr=0.3,0.1

Type RM Length L Ch R = 1 ,58045   ,66,66,66
BEGIN DESCRIPTION:
Buck Creek 58045.29
END DESCRIPTION:
XS GIS Cut Line= 5
      1627750.68      6844832.38      1628068.09      6845447.04
      1628057.69      6845708.14      1628131.91      6845863.09
      1628261.08      6846037.47
#Sta/Elev= 30
  3876.6 1843.24    3973 1838.12  4025.6 1833.25    4142 1830.69  4180.7 1827.04
  4202.9 1827.97  4330.1 1828.24  4402.2 1829.59  4485.2  1829.1  4589.3 1829.89
  4609.4 1828.68  4649.4 1829.47  4699.4  1826.5  4719.5 1827.41  4729.5  1825.9
  4732.1 1824.72  4732.6 1824.22  4746.8 1824.72  4759.5 1829.41  4768.1 1829.84
  4773.1 1828.84  4799.5 1832.95  4832.4  1832.5  4857.7 1833.78    4903 1832.48
  4953.9 1832.41  5035.3 1833.33  5064.5  1831.8  5164.7 1843.83  5218.5 1844.29
#Mann= 3 ,-1 , 0
  3876.6     .05       0  4732.1     .03       0  4746.8     .05       0
Bank Sta=4732.1,4746.8
XS Rating Curve= 0 ,0
Exp/Cntr=0.3,0.1

Type RM Length L Ch R = 1 ,57979   ,173,173,173
BEGIN DESCRIPTION:
Buck Creek 57978.53
END DESCRIPTION:
XS GIS Cut Line= 6
      1627675.16      6844907.91      1628012.05      6845475.43
      1627986.08      6845734.18      1628034.25      6845857.88
      1628085.03      6845909.96      1628223.04      6846076.61
#Sta/Elev= 30
  3875.9 1840.46  3926.4 1838.75  4000.5 1833.09  4160.3  1830.5  4212.9 1828.76
  4240.2 1826.95  4314.2 1826.75  4341.5 1827.63  4548.5 1828.81    4639 1826.71
    4649 1826.22  4655.3  1824.3  4660.3 1825.63  4689.2  1826.8  4719.4 1826.83
  4779.7  1825.8  4795.3 1824.69  4830.6 1825.29  4853.1 1822.55  4853.6 1822.05
  4867.8 1822.55  4914.8 1824.33  4936.4 1823.03  4971.6 1824.75    4993 1823.98
  5007.3 1825.14  5042.4 1830.92  5085.4 1834.63  5155.7 1843.15  5217.8 1844.37
#Mann= 3 ,-1 , 0
  3875.9     .05       0  4853.1     .03       0  4867.8     .05       0
Bank Sta=4853.1,4867.8
XS Rating Curve= 0 ,0
Exp/Cntr=0.3,0.1

Type RM Length L Ch R = 1 ,57806   ,403,403,403
BEGIN DESCRIPTION:
Mapping XS d56d5a14
END DESCRIPTION:
XS GIS Cut Line= 3
      1627732.43      6845493.79      1627854.84      6845842.78
      1628179.44      6846414.07
#Sta/Elev= 30
  4413.6 1830.14  4598.2 1828.92  4677.9    1829  4788.8 1827.75  4816.2 1826.69
  4891.1 1825.17  4904.4 1823.72  4950.3 1823.21  4954.6 1822.12  4955.1 1821.62
  4968.9 1821.62  4969.4 1822.12  4993.5 1824.25  4999.3  1826.7  5020.9 1829.46
    5031 1830.05  5042.5 1831.67  5074.2 1833.75  5101.6 1837.38  5123.2 1839.05
  5182.4 1841.34    5204 1841.41  5226.5 1843.43  5235.7 1843.24  5284.7 1845.24
  5294.8 1845.04  5300.6 1845.73  5316.5 1845.96  5322.2 1846.74  5440.5 1848.26
#Mann= 3 ,-1 , 0
  4413.6     .05       0  4954.6     .05       0  4969.4     .05       0
Bank Sta=4954.6,4969.4
XS Rating Curve= 0 ,0
Exp/Cntr=0.3,0.1

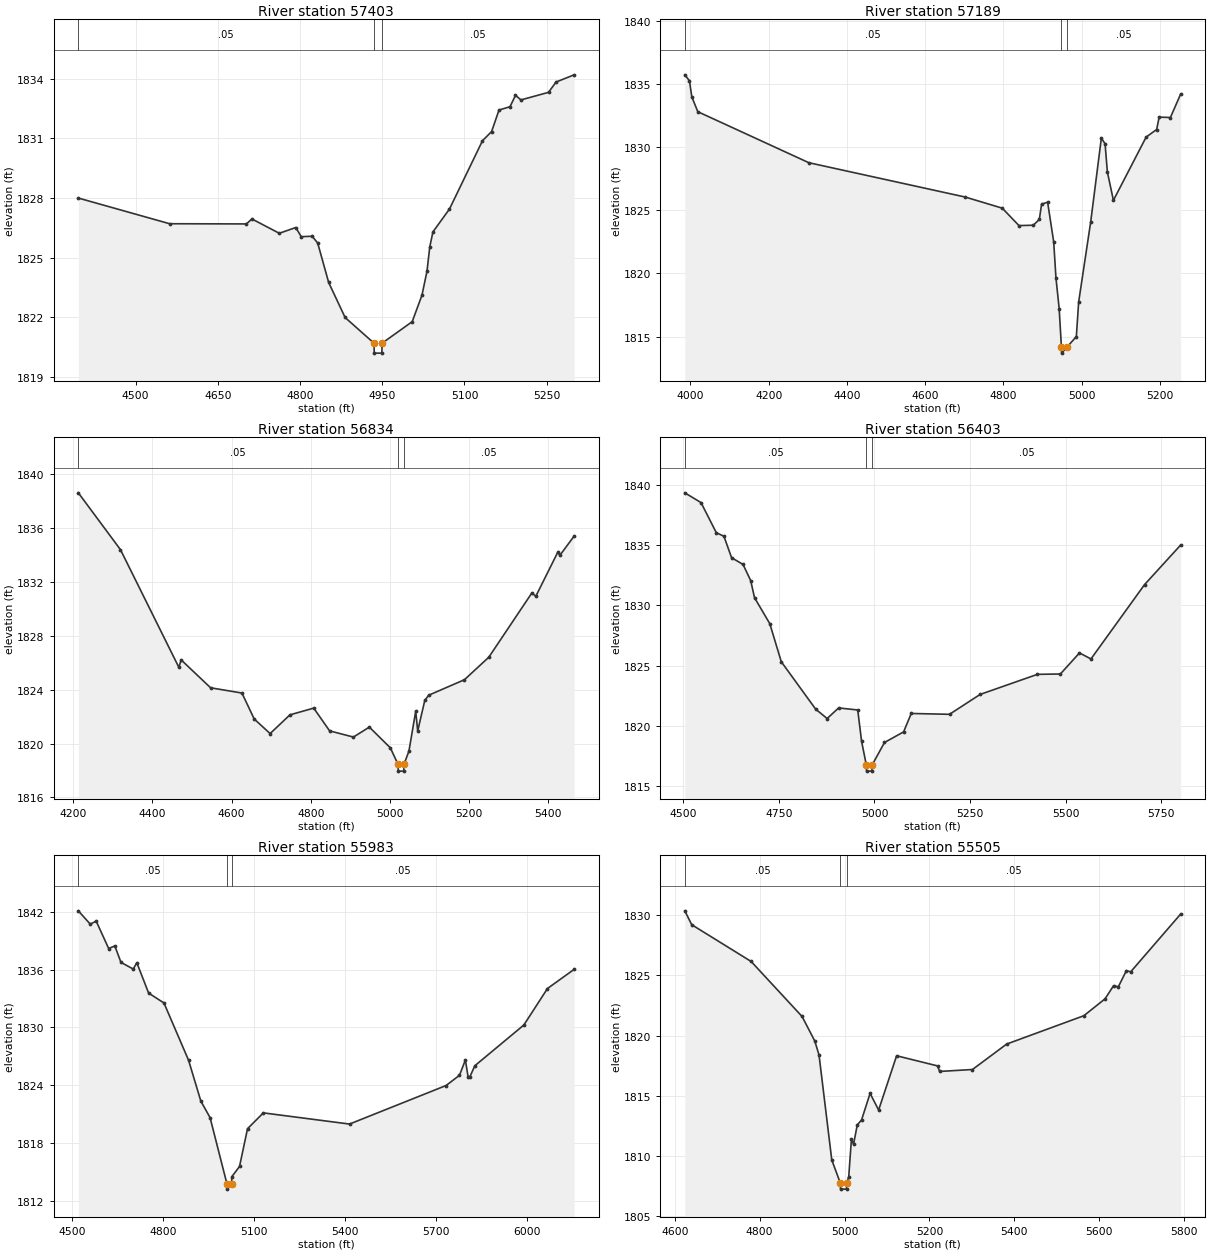
Type RM Length L Ch R = 1 ,57403   ,214,214,214
BEGIN DESCRIPTION:
Buck Creek 57403.22
END DESCRIPTION:
XS GIS Cut Line= 3
      1627694.41      6845711.56      1627677.05      6846317.51
      1627702.96      6846614.59
#Sta/Elev= 30
  4395.7    1828  4562.2 1826.71  4702.3  1826.7  4712.3 1826.95  4762.3 1826.23
  4792.3 1826.52  4802.3 1826.06  4822.3 1826.08  4832.3 1825.74  4852.3 1823.76
  4882.3    1822    4935 1820.71  4935.5 1820.21  4949.3 1820.21  4949.8 1820.71
  5004.7 1821.79  5022.5 1823.12  5031.7 1824.33  5036.7 1825.54  5042.5  1826.3
  5072.7 1827.45  5132.9 1830.88  5149.5 1831.34    5163 1832.42  5183.1 1832.59
  5193.1 1833.16  5203.1 1832.93  5253.3 1833.31  5267.2 1833.83  5300.1 1834.19
#Mann= 3 ,-1 , 0
  4395.7     .05       0    4935     .05       0  4949.8     .05       0
Bank Sta=4935,4949.8
XS Rating Curve= 0 ,0
Exp/Cntr=0.3,0.1

Type RM Length L Ch R = 1 ,57189   ,355,355,355
BEGIN DESCRIPTION:
Mapping XS 01dbdd1c
END DESCRIPTION:
XS GIS Cut Line= 4
      1626993.29      6845603.62      1627475.06      6846384.88
      1627613.95      6846610.57      1627691.02      6846644.82
#Sta/Elev= 30
  3985.7 1835.73  3997.6 1835.26  4003.5    1834  4018.9 1832.81  4302.7 1828.77
  4702.5 1826.05  4797.1 1825.17  4839.7 1823.79  4876.4 1823.82  4891.8 1824.28
  4897.6 1825.49    4913 1825.64  4928.5  1822.5  4934.3 1819.64  4942.5 1817.22
  4948.2 1814.19  4948.7 1813.69  4963.1 1814.19  4986.4    1815  4992.3 1817.74
  5023.1 1824.09  5050.3 1830.72  5059.8 1830.27  5065.7 1828.04  5081.1 1825.79
  5164.8  1830.8  5191.6  1831.4  5198.1 1832.38  5226.8 1832.35  5252.9  1834.2
#Mann= 3 ,-1 , 0
  3985.7     .05       0  4948.2     .03       0  4963.1     .05       0
Bank Sta=4948.2,4963.1
XS Rating Curve= 0 ,0
Exp/Cntr=0.3,0.1

Type RM Length L Ch R = 1 ,56834   ,431,431,431
BEGIN DESCRIPTION:
Buck Creek 56834.4
END DESCRIPTION:
XS GIS Cut Line= 3
      1626471.62      6846636.35      1627258.13       6846686.7
      1627721.68      6846660.75
#Sta/Elev= 30
  4212.9 1838.62  4319.3  1834.4  4466.8 1825.66  4472.7 1826.21    4547 1824.14
  4626.1 1823.75  4657.2 1821.82  4697.3 1820.74  4747.4 1822.13  4807.5 1822.63
  4847.6 1820.94  4907.7 1820.48    4948 1821.22    5001 1819.68  5020.5 1818.45
    5021 1817.95  5034.9 1817.95  5035.4 1818.45    5048 1819.44  5065.1  1822.4
  5070.1 1820.93    5088  1823.2    5098 1823.59  5188.2 1824.74  5249.7 1826.41
  5358.4 1831.18  5368.5 1830.94  5424.3 1834.23  5429.3 1833.98  5465.3 1835.41
#Mann= 3 ,-1 , 0
  4212.9     .05       0  5020.5     .05       0  5035.4     .05       0
Bank Sta=5020.5,5035.4
XS Rating Curve= 0 ,0
Exp/Cntr=0.3,0.1

Type RM Length L Ch R = 1 ,56403   ,420,420,420
BEGIN DESCRIPTION:
Buck Creek 56403.11
END DESCRIPTION:
XS GIS Cut Line= 3
      1626412.64      6846881.14      1626909.17      6846891.56
      1627709.51      6846868.99
#Sta/Elev= 30
  4503.7 1839.36  4546.1 1838.55  4586.1 1836.05  4606.1 1835.75  4626.1 1833.97
  4656.1 1833.41  4676.1 1832.07  4686.1 1830.65  4726.1 1828.49  4756.1 1825.33
  4846.1 1821.39  4876.1 1820.61  4906.2 1821.49  4956.2 1821.32  4966.2 1818.73
  4978.7 1816.74  4979.2 1816.24  4993.2 1816.24  4993.7 1816.74  5026.2 1818.62
  5076.2  1819.5  5096.2 1821.03  5196.3 1820.96  5276.3 1822.61  5426.3 1824.28
  5486.4 1824.31  5536.4 1826.06  5566.4 1825.56  5706.5 1831.73    5801 1835.02
#Mann= 3 ,-1 , 0
  4503.7     .05       0  4978.7     .05       0  4993.7     .05       0
Bank Sta=4978.7,4993.7
XS Rating Curve= 0 ,0
Exp/Cntr=0.3,0.1

Type RM Length L Ch R = 1 ,55983   ,478,478,478
BEGIN DESCRIPTION:
Buck Creek 55983.37
END DESCRIPTION:
XS GIS Cut Line= 3
      1626236.23      6847162.97      1626711.94      6847239.36
      1627819.59      6847558.81
#Sta/Elev= 30
  4521.2  1842.1  4560.5 1840.72  4580.1 1841.03  4621.2 1838.19  4641.5 1838.46
  4661.8 1836.75  4702.3 1836.06    4714 1836.72  4752.9 1833.57  4803.5 1832.54
  4884.6  1826.6  4925.1 1822.36  4955.5 1820.65  5011.5 1813.73    5012 1813.23
  5026.5 1813.73    5027 1814.51  5052.6 1815.58    5079  1819.5  5131.1 1821.14
  5415.2 1819.98  5733.7 1823.98  5777.8 1825.04  5797.2 1826.63  5806.2 1824.86
  5811.4 1824.84  5828.4 1826.03  5990.1 1830.26  6067.8 1834.04  6155.8 1836.03
#Mann= 3 ,-1 , 0
  4521.2     .05       0  5011.5     .05       0  5026.5     .05       0
Bank Sta=5011.5,5026.5
XS Rating Curve= 0 ,0
Exp/Cntr=0.3,0.1

Type RM Length L Ch R = 1 ,55505   ,135,135,135
BEGIN DESCRIPTION:
Buck Creek 55505.01
END DESCRIPTION:
XS GIS Cut Line= 4
      1626378.72      6847697.87      1626755.43      6847701.34
      1627021.06      6847727.38      1627541.81      6847791.39
#Sta/Elev= 30
  4623.7 1830.35    4640  1829.2    4780 1826.15    4900 1821.59    4930 1819.55
    4940 1818.39    4970 1809.69  4990.2 1807.77  4990.7 1807.27  5004.8 1807.27
  5005.3 1807.77    5010 1808.31  5016.3  1811.4  5021.3 1810.99  5030.1 1812.59
  5040.2 1813.01  5060.3 1815.21  5080.4 1813.83  5122.8 1818.33  5219.2 1817.49
  5224.3 1817.03  5301.5 1817.19  5382.1  1819.3  5563.9 1821.65  5613.9 1823.05
    5634 1824.14  5645.2 1824.05  5664.2 1825.39  5674.3 1825.29    5792 1830.08
#Mann= 3 ,-1 , 0
  4623.7     .05       0  4990.2     .05       0  5005.3     .05       0
Bank Sta=4990.2,5005.3
XS Rating Curve= 0 ,0
Exp/Cntr=0.3,0.1