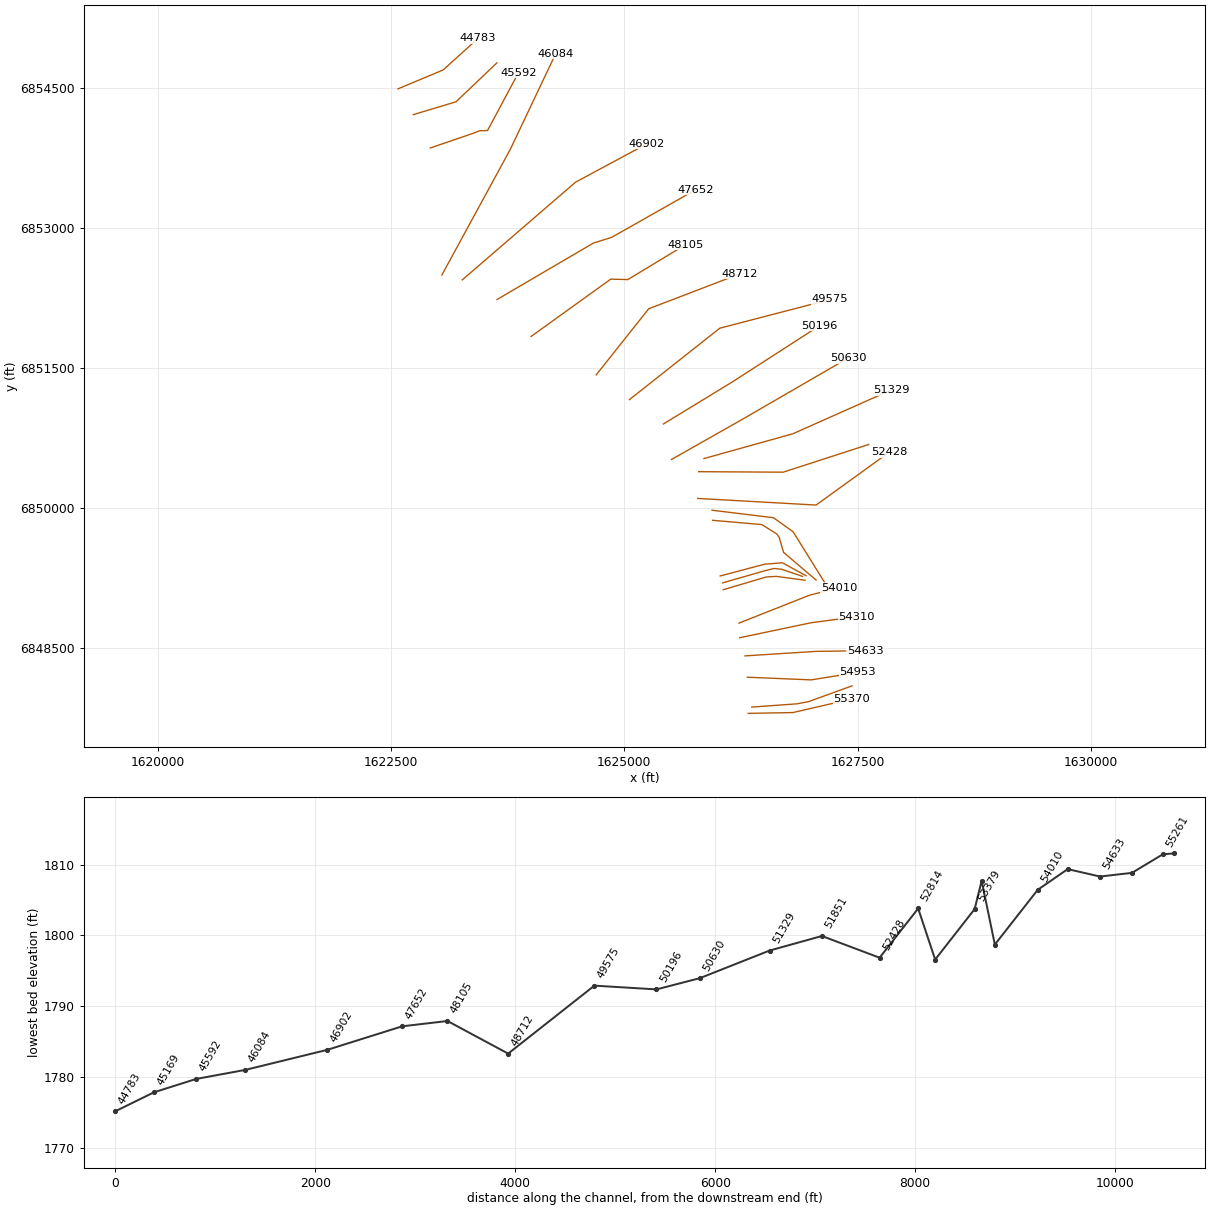
HEC-RAS study Buck Creek.prj: Buck Creek Base Level Engineering

--- Buck Creek.g01 (geometry) --- (continued)

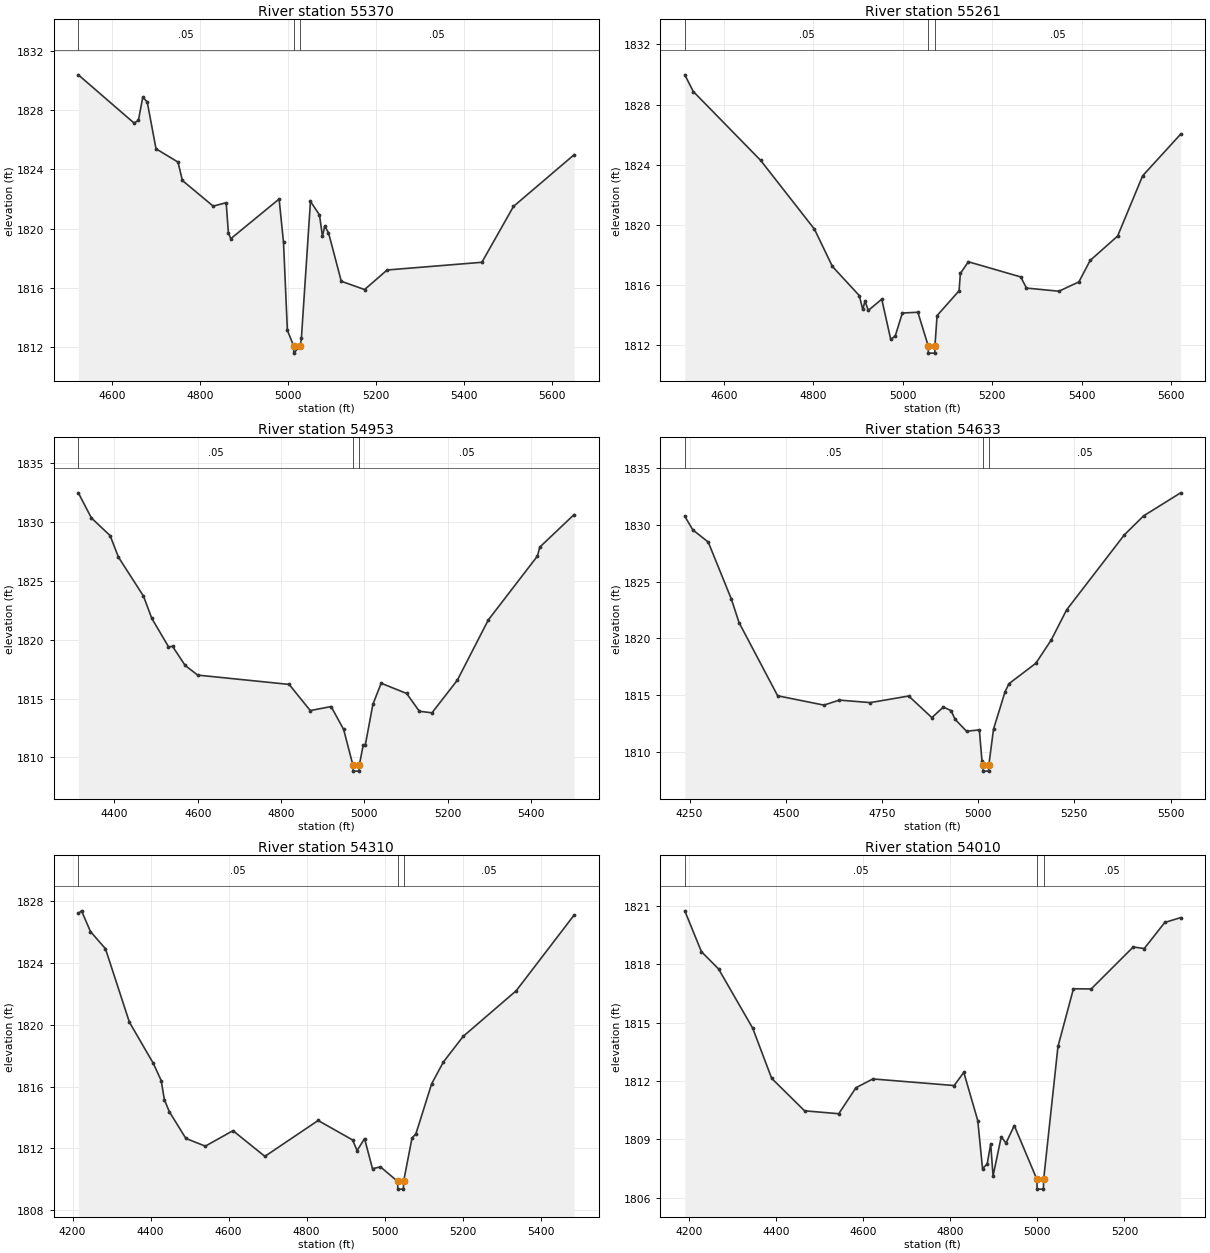
Type RM Length L Ch R = 1 ,55370   ,109,109,109
BEGIN DESCRIPTION:
Buck Creek 55369.73
END DESCRIPTION:
XS GIS Cut Line= 3
      1626328.37      6847796.83      1626807.52      6847805.51
      1627439.49      6847951.35
#Sta/Elev= 30
  4523.2 1830.37  4649.8 1827.12  4659.8 1827.29  4669.8 1828.86  4679.9 1828.54
  4699.9 1825.38  4749.9 1824.48  4759.9 1823.24  4829.9 1821.51  4859.5 1821.74
  4864.5 1819.71  4869.9 1819.31  4979.9 1821.99  4989.9 1819.06  4998.7 1813.13
  5012.8 1812.09  5013.3 1811.59  5027.9 1812.09  5030.6 1812.61  5051.2 1821.83
  5071.7 1820.92  5078.5 1819.47  5083.6 1820.16  5092.2 1819.72  5121.3 1816.44
  5174.3 1815.88  5225.6  1817.2  5441.1 1817.72    5513 1821.49    5651 1824.98
#Mann= 3 ,-1 , 0
  4523.2     .05       0  5012.8     .05       0  5027.9     .05       0
Bank Sta=5012.8,5027.9
XS Rating Curve= 0 ,0
Exp/Cntr=0.3,0.1

Type RM Length L Ch R = 1 ,55261   ,308,308,308
BEGIN DESCRIPTION:
Buck Creek 55261.09
END DESCRIPTION:
XS GIS Cut Line= 4
      1626366.08       6847864.1      1626851.79      6847899.26
      1626975.49      6847922.69      1627440.78      6848091.65
#Sta/Elev= 30
  4512.9 1829.98  4531.9 1828.87  4682.3 1824.29  4802.6 1819.71  4842.7 1817.23
  4902.8 1815.29  4910.5 1814.37  4915.6 1814.92  4922.9  1814.3    4953 1815.05
    4973 1812.38  4983.1  1812.6    4999 1814.13  5033.7 1814.18  5056.6 1811.96
  5057.1 1811.46  5071.4 1811.46  5071.9 1811.96  5076.6 1813.96  5125.8 1815.61
  5128.6 1816.76  5146.5 1817.54  5263.6 1816.53  5276.3 1815.79  5348.7 1815.58
  5393.5  1816.2  5418.7 1817.63    5480 1819.25  5535.9 1823.26  5620.8 1826.03
#Mann= 3 ,-1 , 0
  4512.9     .05       0  5056.6     .05       0  5071.9     .05       0
Bank Sta=5056.6,5071.9
XS Rating Curve= 0 ,0
Exp/Cntr=0.3,0.1

Type RM Length L Ch R = 1 ,54953   ,320,320,320
BEGIN DESCRIPTION:
Buck Creek 54953.07
END DESCRIPTION:
XS GIS Cut Line= 3
      1626318.79      6848184.33       1627003.7      6848155.68
      1627501.84      6848236.11
#Sta/Elev= 30
  4313.5 1832.46    4345 1830.32  4389.8 1828.83  4409.8    1827  4469.8  1823.7
  4489.9  1821.8  4529.9  1819.4  4539.9 1819.42  4569.9 1817.81    4600 1816.99
  4819.5  1816.2  4870.2 1813.98  4920.2 1814.32  4950.3 1812.38  4972.6 1809.34
  4973.1 1808.84  4987.4 1808.84  4987.9 1809.34  4997.2 1811.04  5002.2 1811.04
  5020.6 1814.52  5040.4  1816.3  5101.6 1815.43    5132 1813.92  5162.4 1813.79
  5223.2 1816.56  5297.5 1821.67  5415.6  1827.1    5421 1827.85  5503.6 1830.62
#Mann= 3 ,-1 , 0
  4313.5     .05       0  4972.6     .05       0  4987.9     .05       0
Bank Sta=4972.6,4987.9
XS Rating Curve= 0 ,0
Exp/Cntr=0.3,0.1

Type RM Length L Ch R = 1 ,54633   ,323,323,323
BEGIN DESCRIPTION:
Buck Creek 54632.66
END DESCRIPTION:
XS GIS Cut Line= 3
      1626294.23      6848412.71      1627058.17      6848461.32
      1627581.24      6848468.25
#Sta/Elev= 30
  4237.6 1830.75  4258.4 1829.55  4298.5 1828.48  4358.6 1823.46  4378.6 1821.39
  4478.9 1814.95  4599.1 1814.13  4639.2 1814.57  4719.5 1814.35  4819.5 1814.93
  4879.7 1813.03  4909.7 1813.96  4929.8 1813.64  4939.8 1812.89  4969.8 1811.83
  5003.1 1811.95  5009.9 1809.23  5012.3 1808.82  5012.8 1808.32  5027.1 1808.32
  5027.6 1808.82  5039.9 1812.01  5069.9  1815.3  5079.9 1816.01  5149.9 1817.81
  5189.9 1819.86  5229.9 1822.51  5379.9 1829.11  5429.9 1830.78  5526.2 1832.81
#Mann= 3 ,-1 , 0
  4237.6     .05       0  5012.3     .03       0  5027.6     .05       0
Bank Sta=5012.3,5027.6
XS Rating Curve= 0 ,0
Exp/Cntr=0.3,0.1

Type RM Length L Ch R = 1 ,54310   ,300,300,300
BEGIN DESCRIPTION:
Buck Creek 54310.15
END DESCRIPTION:
XS GIS Cut Line= 3
      1626236.99      6848607.15      1627003.05      6848767.75
      1627486.98      6848832.85
#Sta/Elev= 30
  4214.7  1827.2  4222.9 1827.37  4245.8 1826.03  4284.2 1824.92  4345.6 1820.17
  4406.8 1817.51  4427.2 1816.39  4435.2 1815.16  4447.7 1814.39  4490.3 1812.65
  4540.2 1812.15  4611.1 1813.15  4692.9 1811.49  4829.4 1813.81  4917.7 1812.55
  4929.3 1811.86  4948.3 1812.64  4968.8 1810.69  4989.2 1810.81  5033.2 1809.87
  5033.7 1809.37    5048 1809.37  5048.5 1809.87    5070 1812.67  5080.1 1812.95
  5120.5 1816.19  5150.7  1817.6  5201.2 1819.25  5337.1  1822.2  5485.7  1827.1
#Mann= 3 ,-1 , 0
  4214.7     .05       0  5033.2     .05       0  5048.5     .05       0
Bank Sta=5033.2,5048.5
XS Rating Curve= 0 ,0
Exp/Cntr=0.3,0.1

Type RM Length L Ch R = 1 ,54010   ,429,429,429
BEGIN DESCRIPTION:
Buck Creek 54009.58
END DESCRIPTION:
XS GIS Cut Line= 3
       1626229.6      6848763.83      1626984.82      6849062.45
      1627300.35      6849143.93
#Sta/Elev= 30
    4191 1820.76  4229.1 1818.66  4268.5 1817.77  4346.9 1814.72  4390.4 1812.14
  4465.9 1810.47  4544.3 1810.32  4583.9 1811.66  4622.7 1812.11  4809.3 1811.77
  4831.3 1812.45  4863.4 1809.97  4874.3  1807.5    4885 1807.73  4893.1 1808.77
  4898.5 1807.12  4917.3 1809.13  4928.2 1808.81  4947.2 1809.71  4999.2 1806.94
  4999.7 1806.44  5014.1 1806.44  5014.6 1806.94  5047.5 1813.78    5083 1816.75
  5123.7 1816.74  5220.2  1818.9  5245.6 1818.82  5292.5 1820.16    5329 1820.41
#Mann= 3 ,-1 , 0
    4191     .05       0  4999.2     .05       0  5014.6     .05       0
Bank Sta=4999.2,5014.6
XS Rating Curve= 0 ,0
Exp/Cntr=0.3,0.1

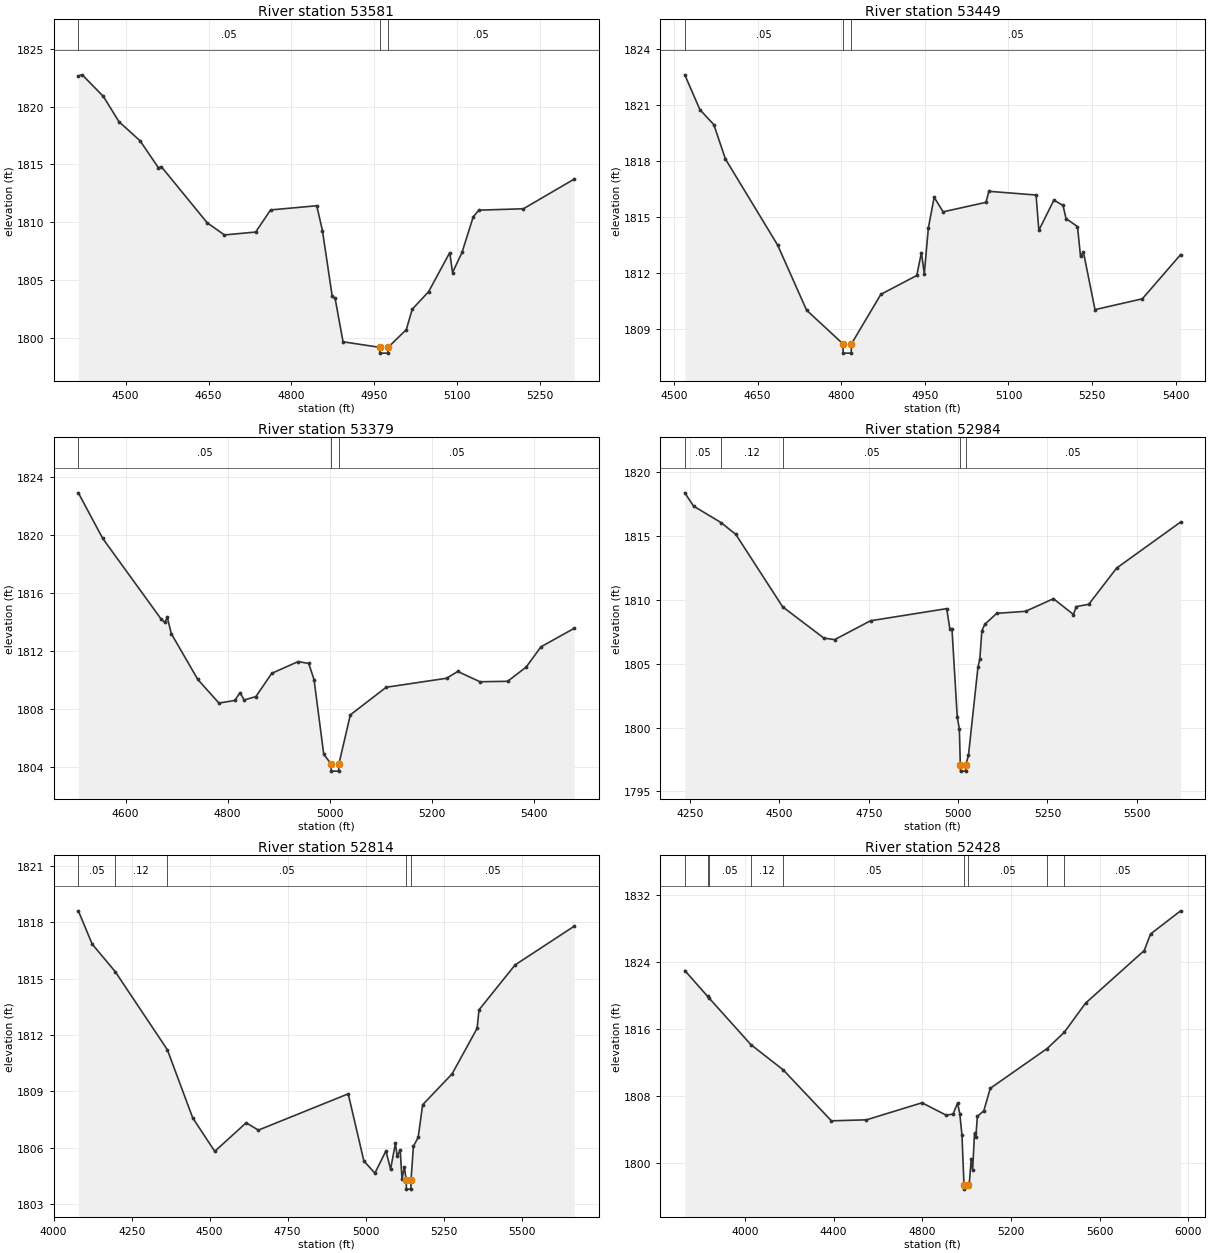
Type RM Length L Ch R = 1 ,53581   ,132,132,132
BEGIN DESCRIPTION:
Buck Creek 53581.01
END DESCRIPTION:
XS GIS Cut Line= 4
      1626061.51      6849121.55      1626521.54      6849258.25
      1626627.87      6849264.77      1626936.08      6849223.53
#Sta/Elev= 30
  4414.3 1822.65  4421.3 1822.74  4459.7 1820.87  4487.7  1818.7  4526.1 1817.04
  4559.3 1814.71  4564.5 1814.81  4647.5 1809.96  4678.7 1808.91  4735.3 1809.16
  4762.2 1811.07  4845.8 1811.43  4856.1 1809.29  4873.8 1803.61    4879 1803.44
  4893.4 1799.68  4959.6  1799.2  4960.1  1798.7  4974.5  1798.7    4975  1799.2
  5007.9 1800.73  5018.6 1802.49  5048.3 1804.01  5086.5 1807.38  5091.6 1805.66
  5108.8 1807.41    5129 1810.47  5139.1 1811.05  5219.8 1811.17  5311.7 1813.73
#Mann= 3 ,-1 , 0
  4414.3     .05       0  4959.6     .05       0    4975     .05       0
Bank Sta=4959.6,4975
XS Rating Curve= 0 ,0
Exp/Cntr=0.3,0.1

Type RM Length L Ch R = 1 ,53449   ,70,70,70
BEGIN DESCRIPTION:
Buck Creek 53449.09
END DESCRIPTION:
XS GIS Cut Line= 5
      1626054.94      6849195.32       1626517.2       6849327.7
      1626606.17       6849349.4      1626688.64      6849340.72
      1626910.03      6849264.75
#Sta/Elev= 30
  4519.4 1822.63  4546.4 1820.77  4571.5 1819.96  4592.3 1818.12  4685.9 1813.51
  4737.9 1810.02    4803 1808.22  4803.5 1807.72  4817.9 1807.72  4818.4 1808.22
  4871.1 1810.87  4935.5 1811.88  4943.8  1813.1    4949 1811.98  4956.3 1814.43
  4966.7 1816.07  4982.8 1815.29  5059.7  1815.8  5064.8 1816.39  5149.5 1816.19
  5154.5  1814.3  5181.5 1815.92  5197.9 1815.63  5203.2 1814.93  5223.8  1814.5
  5229.2 1812.92  5234.5 1813.13  5255.2 1810.05  5340.1 1810.63  5408.8    1813
#Mann= 3 ,-1 , 0
  4519.4     .05       0    4803     .05       0  4818.4     .05       0
Bank Sta=4803,4818.4
XS Rating Curve= 0 ,0
Exp/Cntr=0.3,0.1

Type RM Length L Ch R = 1 ,53379   ,395,395,395
BEGIN DESCRIPTION:
Buck Creek 53378.57
END DESCRIPTION:
XS GIS Cut Line= 4
      1626028.92      6849269.11      1626504.18      6849394.97
      1626695.15      6849410.16      1626947.45      6849272.15
#Sta/Elev= 30
  4507.6  1822.9  4555.3 1819.76  4669.1 1814.23  4676.6 1813.97  4681.8 1814.31
  4689.7 1813.19  4741.5 1810.04  4782.9 1808.41  4813.9 1808.59  4824.2 1809.13
  4832.3 1808.62  4855.3 1808.86  4886.3 1810.46    4938 1811.27  4958.7 1811.14
  4969.1 1810.03  4988.1 1804.88  5002.4 1804.22  5002.9 1803.72  5017.3 1803.72
  5017.8 1804.22  5040.2  1807.6  5110.4  1809.5  5228.6 1810.12  5250.4 1810.59
    5294 1809.88  5348.1 1809.91  5384.4 1810.89  5413.5 1812.29  5478.4 1813.56
#Mann= 3 ,-1 , 0
  4507.6     .05       0  5002.4     .05       0  5017.8     .05       0
Bank Sta=5002.4,5017.8
XS Rating Curve= 0 ,0
Exp/Cntr=0.3,0.1

Type RM Length L Ch R = 1 ,52984   ,170,170,170
BEGIN DESCRIPTION:
Buck Creek 52984.06
END DESCRIPTION:
XS GIS Cut Line= 6
      1625947.12      6849865.24      1626474.44      6849819.67
       1626634.6      6849719.41      1626660.64      6849682.95
      1626707.52      6849521.49      1627055.19       6849225.9
#Sta/Elev= 30
  4235.3  1818.4  4259.8 1817.36  4336.5 1816.07  4378.1 1815.14  4509.2 1809.46
  4624.6 1807.01  4654.7 1806.89  4755.1 1808.37  4968.3 1809.32  4976.9 1807.76
    4983 1807.74  4997.8  1800.8  5003.6  1799.9  5006.4 1797.08  5006.9 1796.58
  5021.3 1796.58  5021.8 1797.08  5029.1 1797.81  5055.7 1804.72    5061 1805.38
  5066.7 1807.59  5074.9 1808.09  5108.2 1808.95    5189 1809.11    5267  1810.1
    5323 1808.86  5330.7 1809.48  5365.8 1809.66  5443.8  1812.5  5622.9 1816.11
#Mann= 5 ,-1 , 0
  4235.3     .05       0  4336.5     .12       0  4509.2     .05       0
  5006.4     .05       0  5021.8     .05       0
Bank Sta=5006.4,5021.8
XS Rating Curve= 0 ,0
Exp/Cntr=0.3,0.1

Type RM Length L Ch R = 1 ,52814   ,386,386,386
BEGIN DESCRIPTION:
Buck Creek 52990.916
END DESCRIPTION:
XS GIS Cut Line= 4
      1625940.96      6849973.42      1626598.47      6849893.13
      1626809.09      6849743.25      1627162.25      6849175.65
#Sta/Elev= 30
  4079.1 1818.61  4123.5 1816.84  4197.1 1815.38  4364.4 1811.22  4445.8 1807.59
  4516.4 1805.81  4617.1 1807.33  4656.2 1806.94  4944.2 1808.87  4994.4  1805.3
  5029.7 1804.65  5065.1 1805.83  5080.1 1804.86  5095.4 1806.23  5101.3 1805.55
  5110.8 1805.89  5116.7 1804.32    5124 1804.98  5130.2  1804.3  5130.7  1803.8
  5145.1  1803.8  5145.6  1804.3  5153.3 1806.08  5168.6 1806.56  5182.8 1808.29
  5277.1 1809.93  5357.5 1812.36  5363.4 1813.34  5479.1 1815.73  5668.5 1817.79
#Mann= 5 ,-1 , 0
  4079.1     .05       0  4197.1     .12       0  4364.4     .05       0
  5130.2     .03       0  5145.6     .05       0
Bank Sta=5130.2,5145.6
XS Rating Curve= 0 ,0
Exp/Cntr=0.3,0.1

Type RM Length L Ch R = 1 ,52428   ,577,577,577
BEGIN DESCRIPTION:
Buck Creek 51987.43
END DESCRIPTION:
XS GIS Cut Line= 3
      1625787.04      6850099.79      1627055.55      6850028.73
      1627838.05       6850593.8
#Sta/Elev= 30
  3729.5 1822.99  3832.4  1819.9  3839.9 1819.67  4027.7 1814.12  4173.1 1811.11
  4390.4 1805.01  4548.7 1805.13  4799.1 1807.17  4909.3 1805.67  4939.4 1805.84
  4959.4 1807.14  4969.4 1805.87  4979.4 1803.27  4988.4 1797.34  4988.9 1796.84
  5006.1 1797.34  5012.6 1797.61  5021.1 1800.47  5027.3 1799.09  5035.8 1803.53
    5042 1803.13  5048.7 1805.55  5077.6  1806.2    5107  1808.9  5363.4 1813.66
  5440.3 1815.59  5536.3 1819.08  5801.1 1825.38  5829.6 1827.36  5965.2 1830.13
#Mann= 9 ,-1 , 0
  3729.5     .05       0  3832.4     .12       0  3839.9     .05       0
  4027.7     .12       0  4173.1     .05       0  4988.4     .05       0
  5006.1     .05       0  5363.4     .12       0  5440.3     .05       0
Bank Sta=4988.4,5006.1
XS Rating Curve= 0 ,0
Exp/Cntr=0.3,0.1

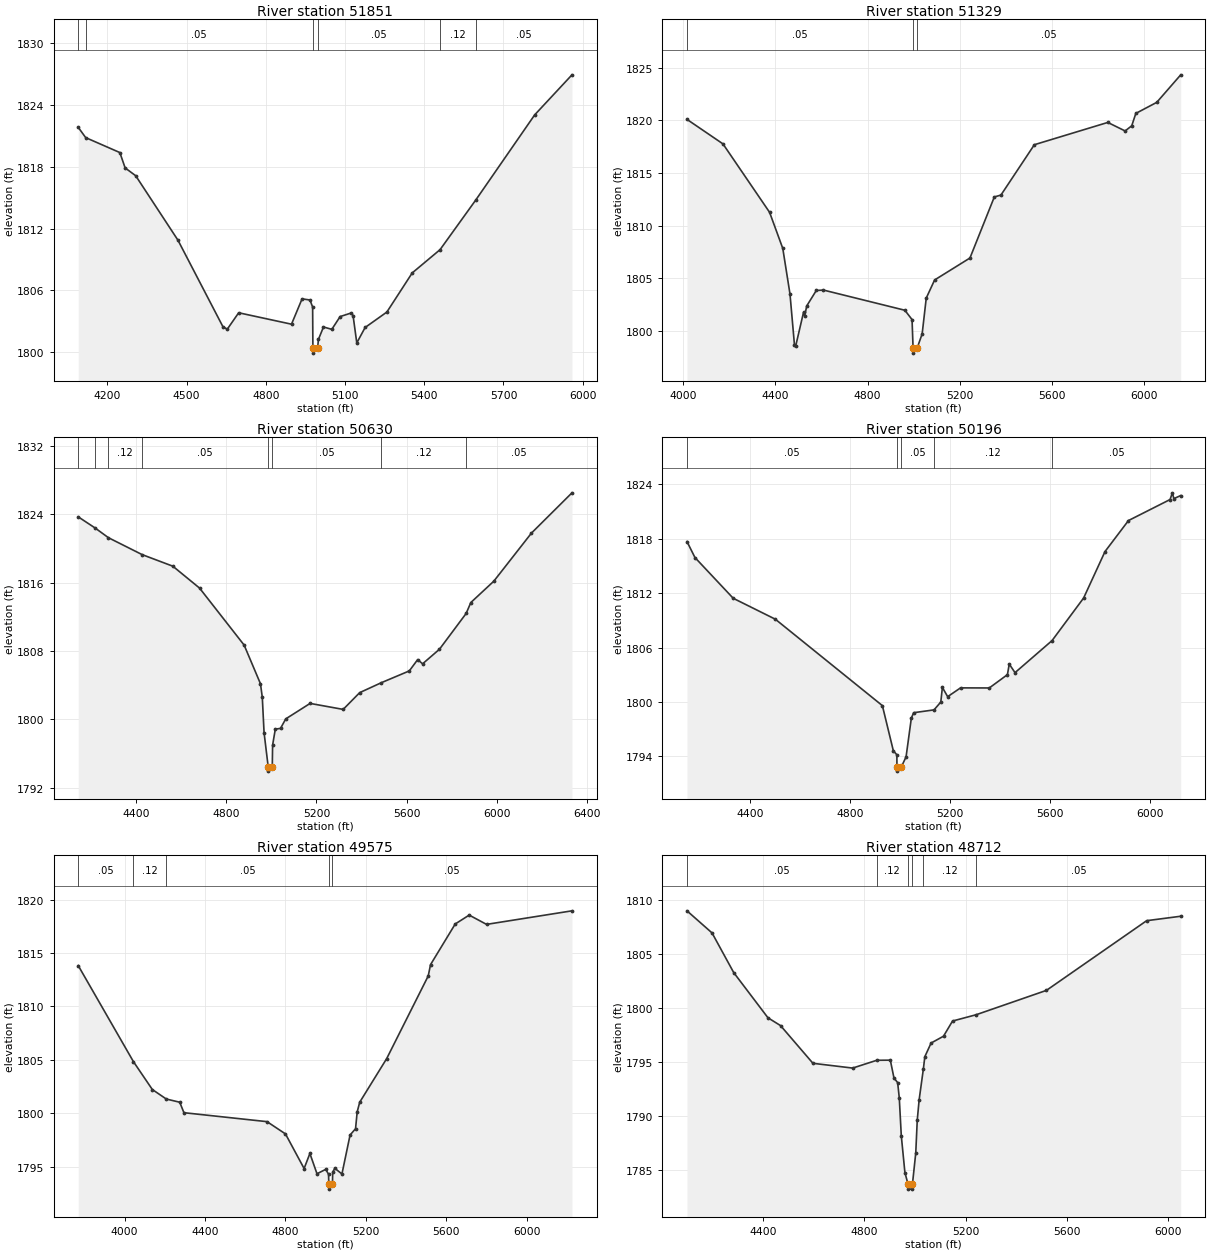
Type RM Length L Ch R = 1 ,51851   ,522,522,522
BEGIN DESCRIPTION:
Buck Creek 51850.89
END DESCRIPTION:
XS GIS Cut Line= 3
      1625797.45      6850386.25      1626703.73      6850381.04
      1627620.17      6850677.85
#Sta/Elev= 30
  4089.8 1821.84  4118.1 1820.84  4247.4 1819.39  4267.4  1817.9  4307.4 1817.14
  4467.4 1810.88  4637.4 1802.49    4654 1802.23  4697.4 1803.83  4897.4 1802.72
  4937.4 1805.18  4967.4 1805.07  4977.4 1804.38  4978.4 1800.41  4978.9 1799.91
  4996.3 1800.41  4999.3 1801.24  5018.5 1802.45    5050 1802.22  5081.5 1803.46
  5123.6 1803.81  5130.5 1803.56  5144.6  1800.9  5176.1  1802.4  5258.5  1803.9
  5354.5  1807.7  5459.9 1809.96  5594.8 1814.77  5818.2 1823.05  5959.4 1826.94
#Mann= 6 ,-1 , 0
  4089.8     .12       0  4118.1     .05       0  4978.4     .05       0
  4996.3     .05       0  5459.9     .12       0  5594.8     .05       0
Bank Sta=4978.4,4996.3
XS Rating Curve= 0 ,0
Exp/Cntr=0.3,0.1

Type RM Length L Ch R = 1 ,51329   ,699,699,699
BEGIN DESCRIPTION:
Buck Creek 51329.32
END DESCRIPTION:
XS GIS Cut Line= 3
      1625854.74      6850526.87       1626807.9       6850792.5
      1627860.02      6851261.27
#Sta/Elev= 30
  4016.6  1820.1  4172.6 1817.77  4374.8 1811.26  4432.1 1807.82  4463.3 1803.49
  4482.6 1798.68  4487.8 1798.51    4522 1801.74  4527.2  1801.4  4535.9 1802.35
  4577.4 1803.82  4608.6 1803.86  4961.5 1801.94  4992.7 1801.05  4997.1 1798.36
  4997.6 1797.86  5015.1 1798.36  5036.5 1799.69  5054.3  1803.1  5090.5 1804.82
  5243.8 1806.91  5349.5 1812.72  5378.2  1812.9  5523.1 1817.69  5841.6 1819.81
  5916.7    1819  5945.4 1819.49  5963.2 1820.67  6053.9 1821.72  6157.9 1824.34
#Mann= 3 ,-1 , 0
  4016.6     .05       0  4997.1     .05       0  5015.1     .05       0
Bank Sta=4997.1,5015.1
XS Rating Curve= 0 ,0
Exp/Cntr=0.3,0.1

Type RM Length L Ch R = 1 ,50630   ,434,434,434
BEGIN DESCRIPTION:
Buck Creek 50630.42
END DESCRIPTION:
XS GIS Cut Line= 3
      1625505.84      6850516.48       1626250.6      6850938.33
      1627401.64        6851605.
#Sta/Elev= 30
  4145.3 1823.69  4219.9 1822.39  4279.1 1821.25  4428.5 1819.27  4564.1 1817.92
  4682.4 1815.36  4879.9 1808.69  4952.2 1804.17  4960.3 1802.58  4968.1 1798.46
  4986.4 1794.45  4986.9 1793.95  5004.5 1794.45  5005.9 1796.99  5017.9 1798.86
    5041 1798.95  5064.1 1800.06    5172 1801.87  5318.3 1801.17  5391.5 1803.13
  5487.1 1804.29  5611.1 1805.67  5648.4    1807  5669.9  1806.5  5744.5  1808.2
  5862.8 1812.39  5883.6 1813.67  5985.5 1816.17    6152 1821.79  6331.4  1826.5
#Mann= 8 ,-1 , 0
  4145.3     .12       0  4219.9     .05       0  4279.1     .12       0
  4428.5     .05       0  4986.4     .05       0  5004.5     .05       0
  5487.1     .12       0  5862.8     .05       0
Bank Sta=4986.4,5004.5
XS Rating Curve= 0 ,0
Exp/Cntr=0.3,0.1

Type RM Length L Ch R = 1 ,50196   ,621,621,621
BEGIN DESCRIPTION:
Buck Creek 50195.99
END DESCRIPTION:
XS GIS Cut Line= 3
      1625420.67      6850897.73      1626155.01      6851345.63
      1627091.27        6851949.
#Sta/Elev= 30
  4148.1  1817.7  4179.9 1815.94  4332.9 1811.44  4501.3 1809.13  4929.3 1799.59
  4973.1 1794.61  4987.3 1794.16  4987.5 1792.86    4988 1792.36  5005.6 1792.86
    5024 1793.93  5045.1 1798.21  5054.3 1798.81  5135.8 1799.12  5162.9 1799.99
  5169.2  1801.6  5190.3 1800.58  5241.8 1801.55  5356.7 1801.54  5429.3 1803.01
  5436.5 1804.18  5459.6 1803.23  5607.7 1806.77  5733.9 1811.47  5819.4  1816.6
  5913.2 1820.02  6079.5 1822.34  6088.7 1823.08  6094.7 1822.44  6122.1 1822.78
#Mann= 5 ,-1 , 0
  4148.1     .05       0  4987.5     .05       0  5005.6     .05       0
  5135.8     .12       0  5607.7     .05       0
Bank Sta=4987.5,5005.6
XS Rating Curve= 0 ,0
Exp/Cntr=0.3,0.1

Type RM Length L Ch R = 1 ,49575   ,863,863,863
BEGIN DESCRIPTION:
Buck Creek 49574.71
END DESCRIPTION:
XS GIS Cut Line= 3
      1625056.06      6851158.13       1626024.8      6851923.75
      1627207.06      6852231.03
#Sta/Elev= 30
  3769.3 1813.83    4044 1804.83    4138 1802.22  4207.5 1801.33  4274.3 1801.03
  4295.1 1800.05  4708.7 1799.21  4800.4 1798.06    4893 1794.82  4921.8 1796.23
  4957.1 1794.33  5000.4 1794.74  5014.6 1794.29  5015.9 1793.39  5016.4 1792.89
    5034 1793.39  5035.3 1794.48  5045.8 1794.84  5081.2 1794.31  5121.7 1797.96
  5148.9 1798.55  5157.1 1800.13  5169.6 1801.03  5303.9 1805.12  5510.5 1812.86
    5522 1813.92  5644.9 1817.73  5714.3 1818.56  5800.6 1817.69  6225.6 1818.96
#Mann= 5 ,-1 , 0
  3769.3     .05       0    4044     .12       0  4207.5     .05       0
  5015.9     .05       0    5034     .05       0
Bank Sta=5015.9,5034
XS Rating Curve= 0 ,0
Exp/Cntr=0.3,0.1

Type RM Length L Ch R = 1 ,48712   ,607,607,607
BEGIN DESCRIPTION:
Buck Creek 48711.51
END DESCRIPTION:
XS GIS Cut Line= 3
      1624700.03      6851423.31      1625262.54      6852131.65
      1626240.83      6852506.31
#Sta/Elev= 30
  4098.4 1808.96  4197.5 1806.92  4283.2 1803.26  4418.6 1799.09  4468.3 1798.37
  4596.4 1794.89  4753.4 1794.45  4848.9 1795.17  4902.4 1795.18  4916.8 1793.53
  4931.3 1793.11  4937.7 1791.71  4945.7 1788.21    4960 1784.81  4971.9 1783.78
  4972.4 1783.28  4989.5 1783.28    4990 1783.78  5002.9 1786.62  5008.8 1789.64
  5016.3 1791.53  5032.9 1794.35  5038.8  1795.5  5063.5 1796.76  5112.6 1797.39
  5148.3 1798.79  5241.4 1799.37  5519.6 1801.62  5915.8 1808.05  6050.5 1808.46
#Mann= 6 ,-1 , 0
  4098.4     .05       0  4848.9     .12       0  4971.9     .05       0
    4990     .12       0  5032.9     .12       0  5241.4     .05       0
Bank Sta=4971.9,4990
XS Rating Curve= 0 ,0
Exp/Cntr=0.3,0.1

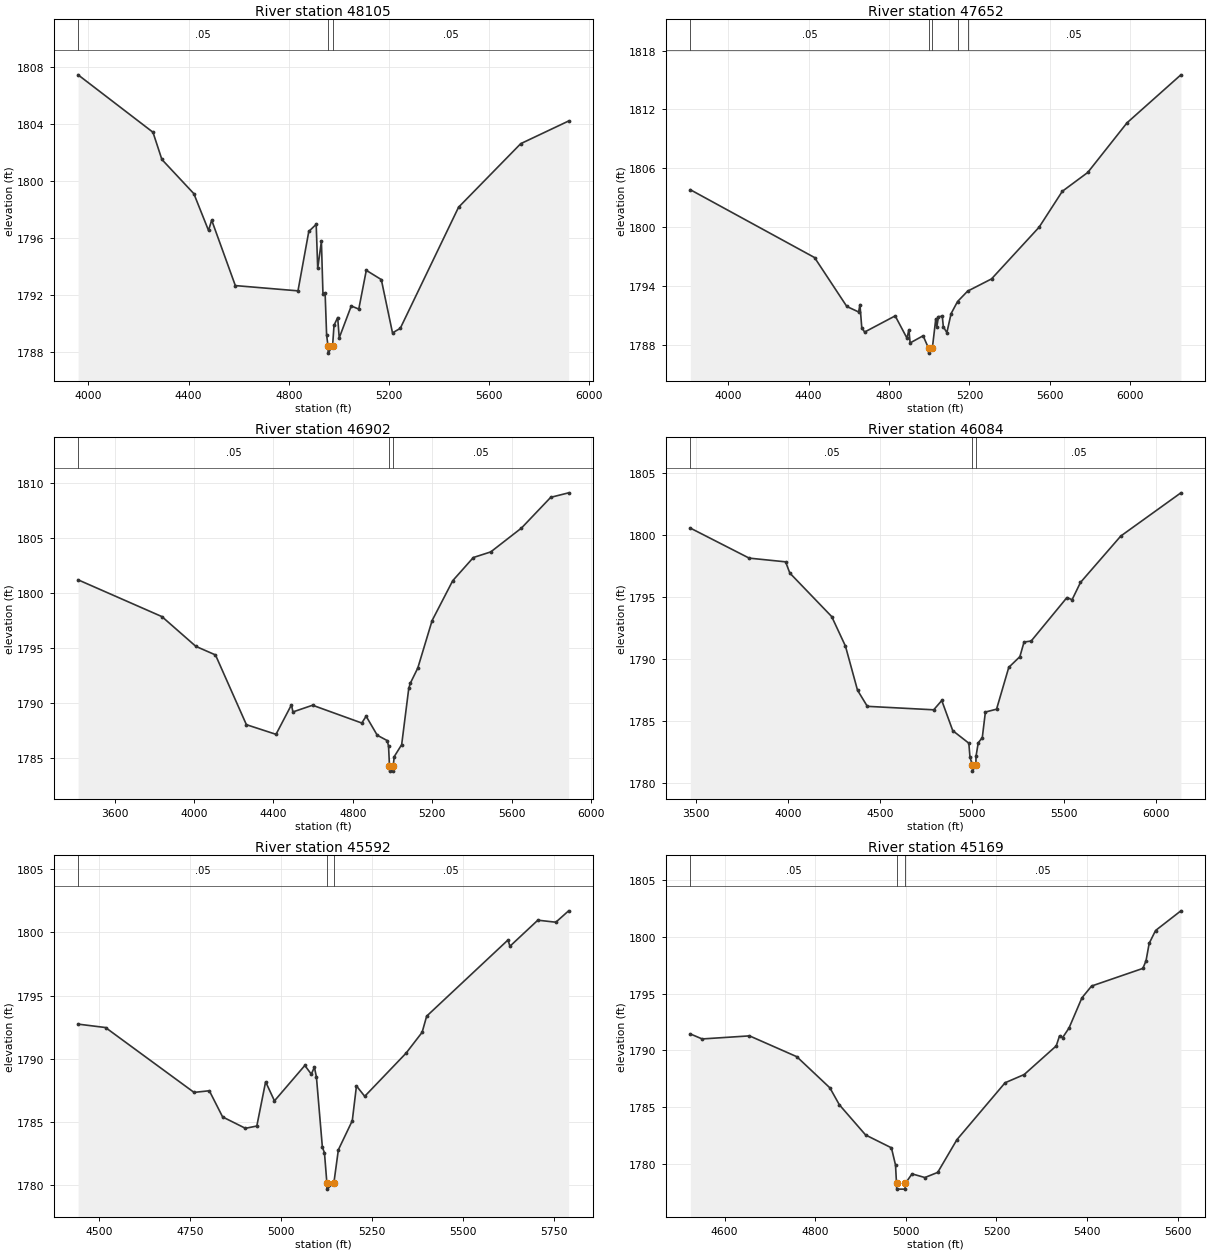
Type RM Length L Ch R = 1 ,48105   ,453,453,453
BEGIN DESCRIPTION:
Buck Creek 48105.32
END DESCRIPTION:
XS GIS Cut Line= 4
      1624002.15      6851834.79      1624856.29      6852449.36
      1625038.58      6852444.15      1625658.34      6852819.13
#Sta/Elev= 30
  3958.7 1807.42  4257.8 1803.39  4293.4 1801.48  4421.1 1799.08  4479.6  1796.5
  4492.3 1797.22  4586.7 1792.63  4836.9 1792.26  4880.1 1796.43  4909.6 1796.93
  4915.7 1793.84  4930.4 1795.74  4936.6 1792.07  4945.2 1792.13  4951.3 1789.14
  4956.9 1788.39  4957.4 1787.89  4975.1 1788.39  4980.8 1789.84  4995.5 1790.39
  5001.6 1788.96  5049.7  1791.2  5079.7 1790.98  5109.7  1793.7  5169.7 1793.05
  5214.4 1789.31  5245.4 1789.63  5478.2 1798.13  5726.5 1802.59  5917.7 1804.18
#Mann= 3 ,-1 , 0
  3958.7     .05       0  4956.9     .05       0  4975.1     .05       0
Bank Sta=4956.9,4975.1
XS Rating Curve= 0 ,0
Exp/Cntr=0.3,0.1

Type RM Length L Ch R = 1 ,47652   ,750,750,750
BEGIN DESCRIPTION:
Buck Creek 47651.96
END DESCRIPTION:
XS GIS Cut Line= 4
      1623637.54      6852230.61      1624668.79      6852834.78
      1624866.71      6852897.28      1625767.74      6853407.68
#Sta/Elev= 30
  3812.4 1803.81  4429.9 1796.89  4590.2  1791.9  4648.9 1791.34  4655.5 1792.09
  4664.5 1789.74  4678.7 1789.29  4830.6 1790.94  4889.2 1788.67  4898.9 1789.53
  4904.9 1788.18  4969.4 1788.91  4996.4 1787.64  4996.9 1787.14  5015.3 1787.64
  5032.4 1790.64  5037.6 1789.81  5045.6 1790.86  5064.7  1790.9    5070 1789.83
  5087.5 1789.23  5108.5 1791.17  5140.5  1792.4  5190.4 1793.46  5309.4 1794.71
  5546.1 1799.99  5661.4 1803.65  5787.8 1805.57  5983.2 1810.64  6250.7 1815.53
#Mann= 5 ,-1 , 0
  3812.4     .05       0  4996.4     .05       0  5015.3     .05       0
  5140.5     .12       0  5190.4     .05       0
Bank Sta=4996.4,5015.3
XS Rating Curve= 0 ,0
Exp/Cntr=0.3,0.1

Type RM Length L Ch R = 1 ,46902   ,818,818,818
BEGIN DESCRIPTION:
Buck Creek 46902.12
END DESCRIPTION:
XS GIS Cut Line= 3
       1623265.3       6852441.1      1624478.88        6853488.
      1625244.49      6853899.45
#Sta/Elev= 30
  3415.4 1801.23  3837.9 1797.88    4009 1795.17  4107.8 1794.39  4263.6 1788.04
  4412.8 1787.16  4490.7 1789.85    4498  1789.2  4597.1 1789.81    4845 1788.19
  4866.9 1788.81  4922.9 1787.08  4973.3 1786.59  4979.9 1786.08  4984.6 1784.31
  4985.1 1783.81  5003.2 1783.81  5003.7 1784.31  5008.4 1785.13    5046 1786.22
  5081.8 1791.35  5089.8 1791.82  5127.3  1793.2  5199.4 1797.52  5303.3 1801.15
  5407.2 1803.26  5494.8 1803.77  5649.5 1805.94  5797.1 1808.74  5887.3 1809.15
#Mann= 3 ,-1 , 0
  3415.4     .05       0  4984.6     .05       0  5003.7     .05       0
Bank Sta=4984.6,5003.7
XS Rating Curve= 0 ,0
Exp/Cntr=0.3,0.1

Type RM Length L Ch R = 1 ,46084   ,492,492,492
BEGIN DESCRIPTION:
Buck Creek 46084.35
END DESCRIPTION:
XS GIS Cut Line= 3
      1623046.61      6852493.25      1623780.96      6853842.17
      1624265.34      6854863.02
#Sta/Elev= 30
  3469.3 1800.56    3789 1798.14  3987.1 1797.84  4009.8 1796.94  4237.6 1793.43
  4312.3 1791.05  4377.8  1787.5  4431.1  1786.2  4791.9 1785.92  4835.6 1786.67
  4895.4 1784.24  4982.8 1783.23    4989  1782.1    5002 1781.48  5002.5 1780.98
  5021.2 1781.48  5021.7 1782.16  5033.8 1783.26  5055.9 1783.68  5072.7 1785.74
  5133.4 1785.97  5199.8 1789.34  5260.1  1790.2  5282.8 1791.38  5321.5 1791.46
  5515.7 1794.96  5543.9 1794.79  5589.4 1796.18  5808.6 1799.92  6135.1  1803.4
#Mann= 3 ,-1 , 0
  3469.3     .05       0    5002     .05       0  5021.2     .05       0
Bank Sta=5002,5021.2
XS Rating Curve= 0 ,0
Exp/Cntr=0.3,0.1

Type RM Length L Ch R = 1 ,45592   ,423,423,423
BEGIN DESCRIPTION:
Buck Creek 45592.21
END DESCRIPTION:
XS GIS Cut Line= 5
      1622923.68      6853854.53      1623385.96      6854012.96
      1623451.06        6854039.       1623535.7      6854041.17
      1623867.71      6854661.79
#Sta/Elev= 30
  4443.1 1792.75  4518.5 1792.48  4761.6 1787.35  4803.6 1787.48  4840.1 1785.41
  4902.7 1784.51    4934 1784.69  4958.2 1788.19  4982.5 1786.68  5065.9 1789.48
  5083.7 1788.79  5092.2 1789.35  5097.8 1788.55  5114.1 1783.01  5119.8 1782.58
  5126.4  1780.2  5126.9  1779.7  5145.7  1780.2    5158 1782.81  5196.2 1785.11
  5207.7 1787.86  5230.4 1787.04  5343.8 1790.45    5388  1792.1  5400.5 1793.38
  5623.7  1799.4  5629.3 1798.91  5705.8 1800.97  5755.3 1800.81  5790.4 1801.71
#Mann= 3 ,-1 , 0
  4443.1     .05       0  5126.4     .05       0  5145.7     .05       0
Bank Sta=5126.4,5145.7
XS Rating Curve= 0 ,0
Exp/Cntr=0.3,0.1

Type RM Length L Ch R = 1 ,45169   ,386,386,386
BEGIN DESCRIPTION:
Buck Creek 45169.15
END DESCRIPTION:
XS GIS Cut Line= 3
      1622739.98      6854211.32      1623198.28      6854349.33
      1623635.78        6854766.
#Sta/Elev= 30
  4524.2 1791.45  4550.3 1791.01  4654.8 1791.28  4759.2 1789.45  4832.3 1786.71
  4853.2 1785.22  4911.1 1782.57  4968.1 1781.44  4977.1 1779.93  4979.3 1778.31
  4979.8 1777.81  4998.2 1777.81  4998.7 1778.31  5013.6 1779.15  5041.9 1778.83
  5070.2 1779.28  5112.7 1782.16    5219 1787.16  5261.1 1787.88  5331.9  1790.4
  5339.1 1791.28    5346 1791.13  5360.2 1791.98  5388.5 1794.62  5409.9 1795.66
  5523.1 1797.21  5530.1 1797.89    5537 1799.41  5551.1 1800.54    5607 1802.27
#Mann= 3 ,-1 , 0
  4524.2     .05       0  4979.3     .05       0  4998.7     .05       0
Bank Sta=4979.3,4998.7
XS Rating Curve= 0 ,0
Exp/Cntr=0.3,0.1

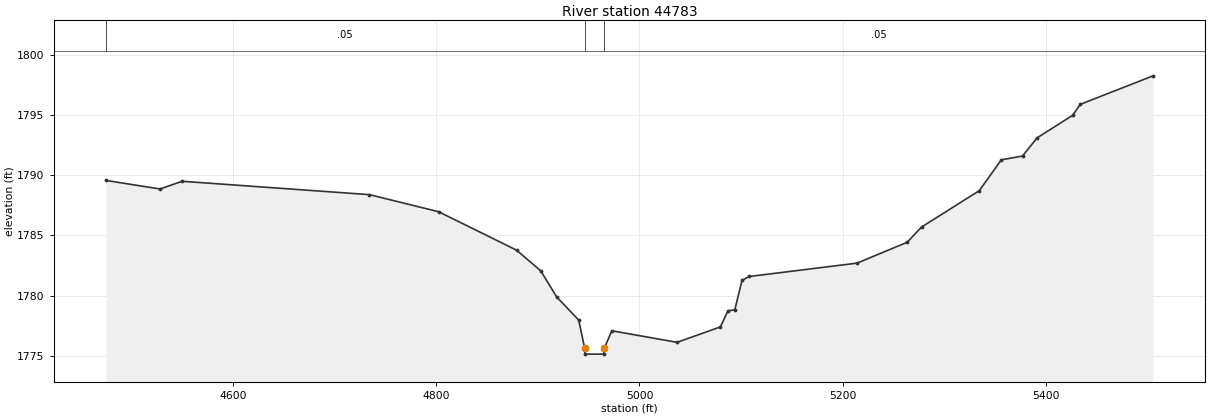
Type RM Length L Ch R = 1 ,44783   ,662,662,662
BEGIN DESCRIPTION:
Buck Creek 44782.72
END DESCRIPTION:
XS GIS Cut Line= 3
      1622575.86      6854487.34      1623060.26      6854690.48
      1623435.28      6855029.04
#Sta/Elev= 30
  4474.9 1789.56  4528.2 1788.85  4549.9 1789.49  4734.2 1788.38  4802.3 1786.96
    4879 1783.77  4902.8 1782.05  4918.6 1779.87  4940.2 1777.96    4946 1775.63
  4946.5 1775.13  4964.9 1775.13  4965.4 1775.63  4972.8 1777.07    5037 1776.11
  5079.6 1777.39  5087.1 1778.73  5093.8 1778.81  5100.9 1781.26    5108 1781.58
  5214.1 1782.69  5263.4 1784.42  5277.6 1785.69  5334.4 1788.71  5356.1 1791.27
    5377 1791.59  5391.2 1793.09  5426.4 1794.98  5433.8 1795.88  5505.4 1798.25
#Mann= 3 ,-1 , 0
  4474.9     .05       0    4946     .05       0  4965.4     .05       0
Bank Sta=4946,4965.4
XS Rating Curve= 0 ,0
Exp/Cntr=0.3,0.1