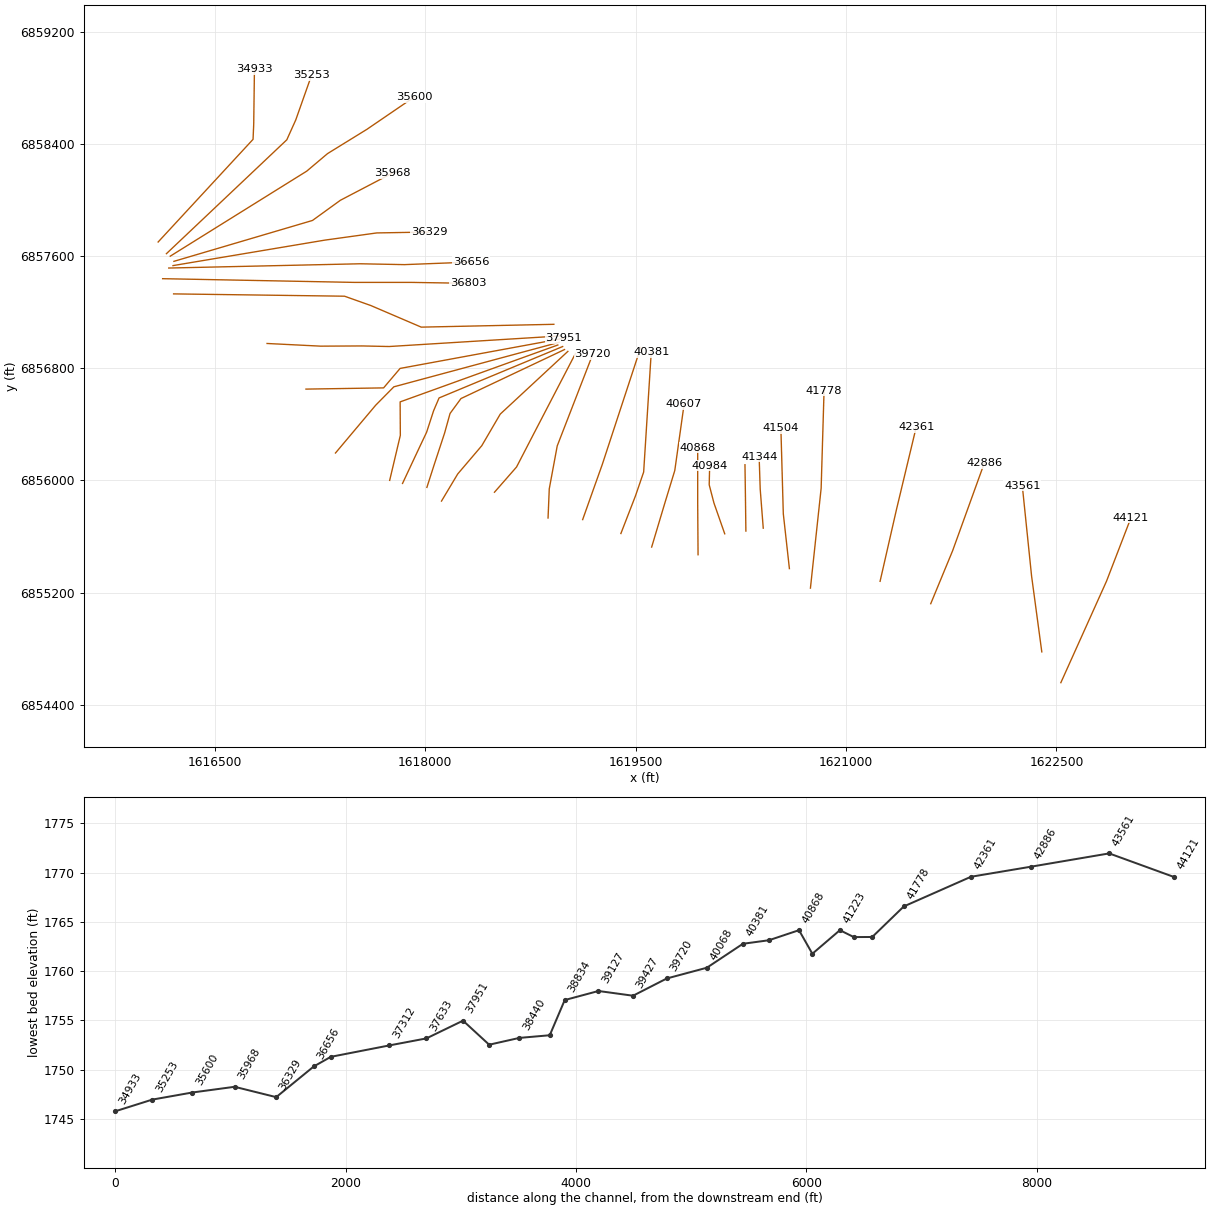
HEC-RAS study Buck Creek.prj: Buck Creek Base Level Engineering

--- Buck Creek.g01 (geometry) --- (continued)

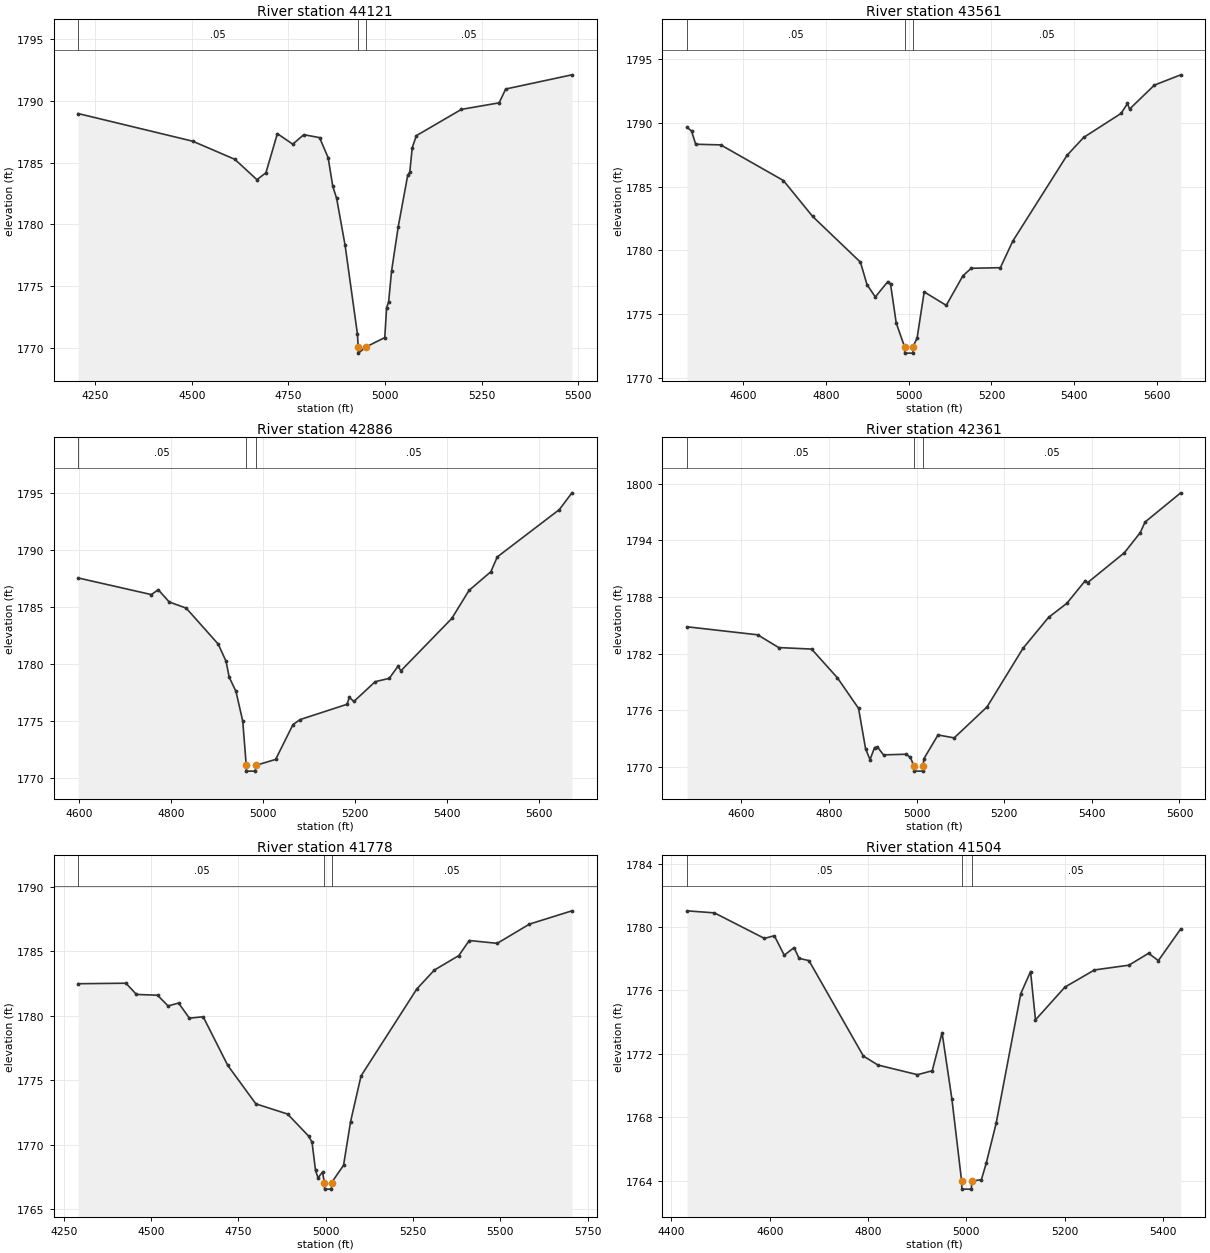
Type RM Length L Ch R = 1 ,44121   ,560,560,560
BEGIN DESCRIPTION:
Buck Creek 44120.74
END DESCRIPTION:
XS GIS Cut Line= 3
      1622531.62      6854557.69      1622857.13      6855281.62
      1623031.29       6855733.9
#Sta/Elev= 30
  4205.7 1788.98  4502.1 1786.74  4611.3 1785.27  4668.5 1783.62  4691.7 1784.18
  4721.4 1787.35  4761.2  1786.5  4789.8 1787.27  4830.6 1787.03  4852.9  1785.4
  4864.8 1783.09  4874.9  1782.1  4896.8 1778.29  4928.7 1771.11  4930.6 1770.06
  4931.1 1769.56  4950.8 1770.06  4999.5 1770.82  5004.2 1773.23  5009.5 1773.72
    5017 1776.19  5034.2 1779.78  5058.8 1783.96  5064.2 1784.23  5070.6 1786.21
  5081.3 1787.19    5198 1789.32  5295.6 1789.85  5312.6 1790.97  5484.1 1792.12
#Mann= 3 ,-1 , 0
  4205.7     .05       0  4930.6     .05       0  4950.8     .05       0
Bank Sta=4930.6,4950.8
XS Rating Curve= 0 ,0
Exp/Cntr=0.3,0.1

Type RM Length L Ch R = 1 ,43561   ,675,675,675
BEGIN DESCRIPTION:
Buck Creek 43560.9
END DESCRIPTION:
XS GIS Cut Line= 3
      1622395.79      6854777.32      1622322.88      6855318.95
       1622256.9      6855961.36
#Sta/Elev= 30
    4465 1789.66  4475.8 1789.39  4485.9 1788.34  4546.4 1788.29  4697.8 1785.49
  4768.4 1782.67  4883.8 1779.08  4899.6 1777.32  4919.7 1776.35    4950 1777.56
  4956.6 1777.33  4970.2 1774.31  4990.3 1772.44  4990.8 1771.94  5010.1 1771.94
  5010.6 1772.44  5020.6 1773.12  5037.7 1776.75    5091 1775.69  5131.2 1778.01
  5151.3  1778.6  5221.7 1778.65  5251.8 1780.74  5382.5 1787.46  5422.7 1788.87
  5513.2 1790.76  5528.7 1791.54  5533.7  1791.1  5593.6 1792.98  5657.3 1793.79
#Mann= 3 ,-1 , 0
    4465     .05       0  4990.3     .05       0  5010.6     .05       0
Bank Sta=4990.3,5010.6
XS Rating Curve= 0 ,0
Exp/Cntr=0.3,0.1

Type RM Length L Ch R = 1 ,42886   ,525,525,525
BEGIN DESCRIPTION:
Buck Creek 42885.63
END DESCRIPTION:
XS GIS Cut Line= 3
      1621604.14      6855121.05      1621760.38       6855499.5
      1621985.79      6856123.71
#Sta/Elev= 30
  4598.6 1787.57  4757.6 1786.11  4772.5 1786.54  4796.4 1785.46  4833.3 1784.92
  4902.9 1781.76  4919.9 1780.25  4926.8 1778.85  4941.5  1777.6  4956.2 1774.99
  4963.8  1771.1  4964.3  1770.6  4983.6  1770.6  4984.1  1771.1  5027.7 1771.63
  5065.4 1774.69  5080.9 1775.13  5182.7 1776.47    5188 1777.07  5197.8 1776.72
  5244.1 1778.46  5274.7 1778.75  5293.5 1779.81  5300.1 1779.42  5410.5 1784.01
  5448.1 1786.48  5495.5 1788.12  5509.5 1789.42  5644.4 1793.58  5671.7 1795.05
#Mann= 3 ,-1 , 0
  4598.6     .05       0  4963.8     .05       0  4984.1     .05       0
Bank Sta=4963.8,4984.1
XS Rating Curve= 0 ,0
Exp/Cntr=0.3,0.1

Type RM Length L Ch R = 1 ,42361   ,583,583,583
BEGIN DESCRIPTION:
Buck Creek 42360.7
END DESCRIPTION:
XS GIS Cut Line= 3
      1621243.02      6855280.76      1621361.08      6855798.12
      1621499.96      6856377.96
#Sta/Elev= 30
    4476 1784.85  4637.2    1784  4685.3 1782.65  4760.4 1782.49  4819.4 1779.44
  4867.5 1776.21  4883.5 1771.95  4893.7 1770.78    4904 1772.07  4910.5 1772.13
  4924.5 1771.29  4975.8 1771.36    4986 1771.02    4994 1770.07  4994.5 1769.57
  5013.9 1769.57  5014.4 1770.07  5016.8  1770.9  5048.9  1773.4  5085.8 1773.09
  5160.8 1776.37    5243 1782.58  5301.1 1785.84  5343.1 1787.34  5385.1 1789.74
  5390.3 1789.52  5474.3 1792.69  5510.4 1794.81  5521.5 1795.94  5602.9 1799.03
#Mann= 3 ,-1 , 0
    4476     .05       0    4994     .05       0  5014.4     .05       0
Bank Sta=4994,5014.4
XS Rating Curve= 0 ,0
Exp/Cntr=0.3,0.1

Type RM Length L Ch R = 1 ,41778   ,274,274,274
BEGIN DESCRIPTION:
Buck Creek 41777.79
END DESCRIPTION:
XS GIS Cut Line= 3
      1620746.49      6855232.15      1620822.88      6855943.95
      1620843.71      6856641.85
#Sta/Elev= 30
  4291.2 1782.48  4427.8 1782.52    4458 1781.65  4518.3 1781.59  4548.5 1780.76
  4578.7 1780.98  4609.6 1779.81  4649.1 1779.92  4719.5 1776.15    4800 1773.17
  4890.9 1772.38  4950.8 1770.68  4960.9  1770.2  4970.9 1768.01    4978 1767.44
    4991 1767.88  4996.4 1767.06  4996.9 1766.56  5016.3 1766.56  5016.8 1767.06
  5051.2 1768.41  5071.2 1771.78  5101.2 1775.33  5261.2 1782.08  5311.3 1783.54
  5381.3 1784.66  5411.3 1785.83  5491.4 1785.61  5583.6  1787.1  5705.3 1788.13
#Mann= 3 ,-1 , 0
  4291.2     .05       0  4996.4     .05       0  5016.8     .05       0
Bank Sta=4996.4,5016.8
XS Rating Curve= 0 ,0
Exp/Cntr=0.3,0.1

Type RM Length L Ch R = 1 ,41504   ,160,160,160
BEGIN DESCRIPTION:
Mapping XS 499b1676
END DESCRIPTION:
XS GIS Cut Line= 3
      1620596.59      6855371.43      1620553.19      6855762.05
      1620535.84      6856373.48
#Sta/Elev= 30
  4431.7 1781.02  4487.5 1780.89  4589.2 1779.28  4609.4 1779.45  4629.5 1778.22
  4649.6  1778.7  4659.7 1778.02  4679.8 1777.88  4790.5 1771.86  4820.2 1771.29
  4900.7 1770.68  4930.7 1770.93  4950.7 1773.33  4970.7 1769.15  4990.5 1763.96
    4991 1763.46  5010.4 1763.46  5010.9 1763.96  5030.8 1764.06  5040.8 1765.12
  5060.8 1767.62  5110.8 1775.79  5130.8 1777.19  5140.8 1774.14  5200.8 1776.21
  5260.9 1777.29  5330.9 1777.59  5370.9 1778.34  5390.9 1777.88  5436.4 1779.88
#Mann= 3 ,-1 , 0
  4431.7     .05       0  4990.5     .05       0  5010.9     .05       0
Bank Sta=4990.5,5010.9
XS Rating Curve= 0 ,0
Exp/Cntr=0.3,0.1

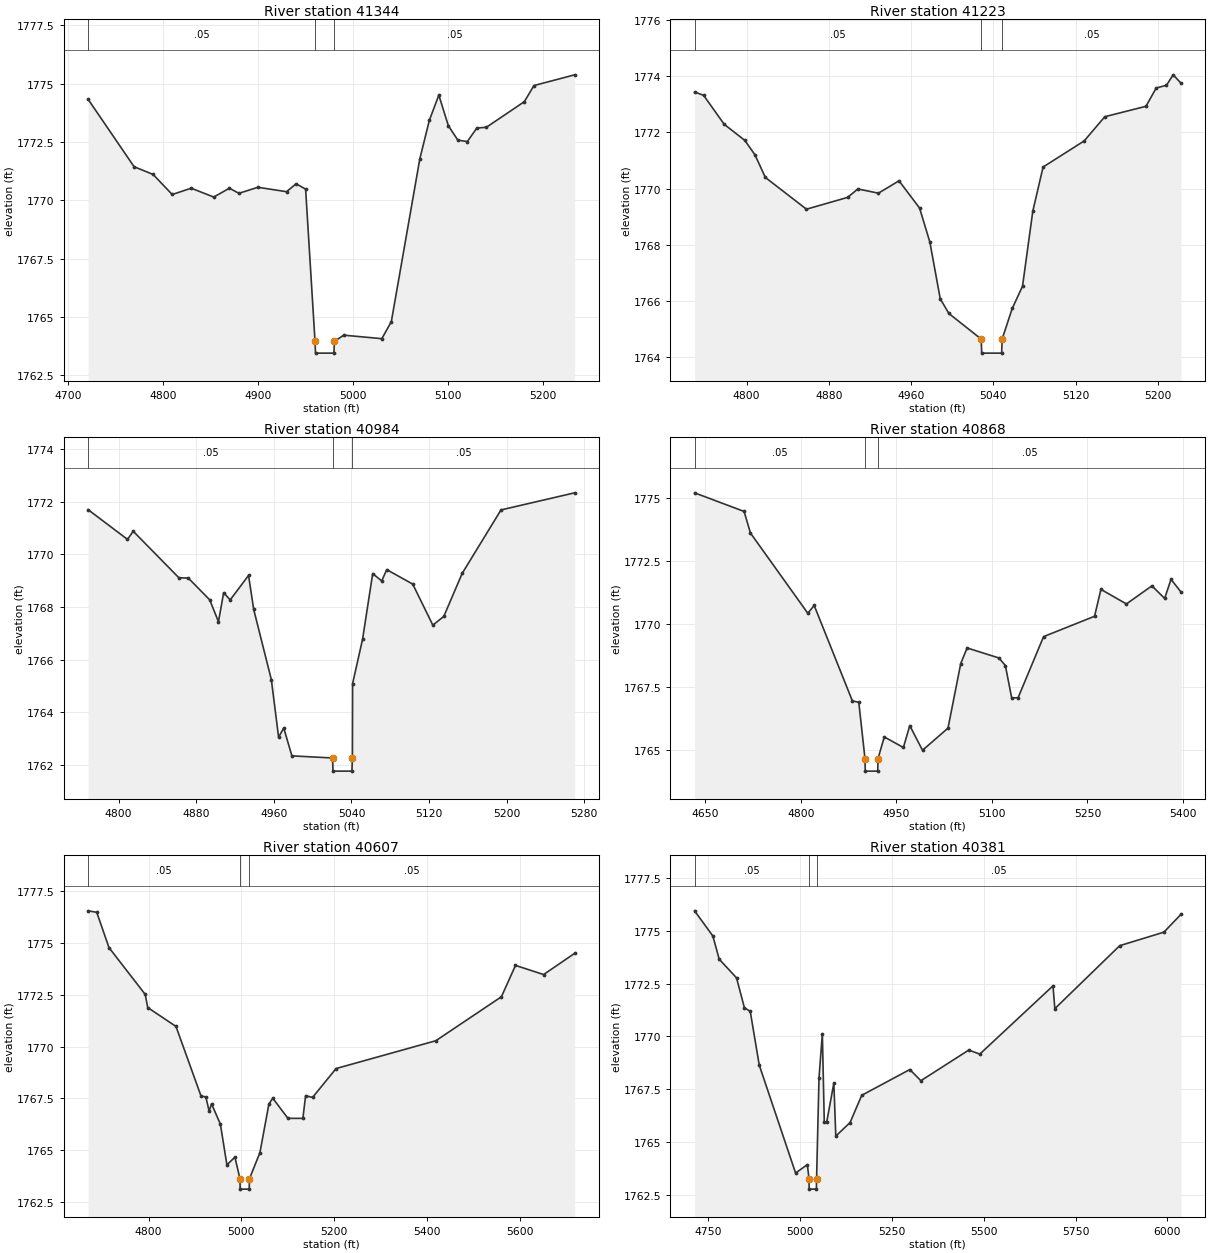
Type RM Length L Ch R = 1 ,41344   ,121,121,121
BEGIN DESCRIPTION:
Buck Creek 41344.26
END DESCRIPTION:
XS GIS Cut Line= 3
      1620410.12      6855659.79      1620388.42      6855939.72
      1620380.82      6856170.82
#Sta/Elev= 30
  4721.5 1774.33  4769.9 1771.44  4789.9 1771.11    4810 1770.25    4830 1770.52
  4853.7 1770.14  4870.2 1770.52  4880.2  1770.3  4900.2 1770.56  4930.3 1770.37
  4940.4 1770.71  4950.4 1770.48  4960.3 1763.95  4960.8 1763.45  4980.2 1763.45
  4980.7 1763.95  4990.5 1764.22  5030.6 1764.07  5040.6  1764.8  5070.6 1771.78
  5080.6 1773.43  5090.6 1774.51  5100.6  1773.2  5110.6 1772.58  5120.6 1772.52
  5130.6  1773.1  5140.6 1773.13  5180.6 1774.23  5190.7 1774.92  5233.5 1775.38
#Mann= 3 ,-1 , 0
  4721.5     .05       0  4960.3     .05       0  4980.7     .05       0
Bank Sta=4960.3,4980.7
XS Rating Curve= 0 ,0
Exp/Cntr=0.3,0.1

Type RM Length L Ch R = 1 ,41223   ,239,239,239
BEGIN DESCRIPTION:
Buck Creek 41223.36
END DESCRIPTION:
XS GIS Cut Line= 3
      1620286.42      6855639.17      1620283.16      6855889.81
      1620279.91      6856112.23
#Sta/Elev= 30
  4749.4 1773.44  4758.2 1773.32  4778.2 1772.29  4798.2 1771.72  4808.2  1771.2
  4818.2  1770.4  4858.2 1769.27  4898.2 1769.69  4908.2 1769.99  4928.2 1769.84
  4948.2 1770.28  4968.2 1769.31  4978.2  1768.1  4988.3 1766.08  4996.7 1765.56
  5028.1 1764.65  5028.6 1764.15    5048 1764.15  5048.5 1764.65  5058.3 1765.74
  5068.3 1766.53  5078.3  1769.2  5088.3 1770.77  5128.3  1771.7  5148.3 1772.56
  5188.3 1772.93  5198.3 1773.58  5208.3 1773.68  5214.8 1774.05  5222.5 1773.75
#Mann= 3 ,-1 , 0
  4749.4     .05       0  5028.1     .05       0  5048.5     .05       0
Bank Sta=5028.1,5048.5
XS Rating Curve= 0 ,0
Exp/Cntr=0.3,0.1

Type RM Length L Ch R = 1 ,40984   ,116,116,116
BEGIN DESCRIPTION:
Buck Creek 40983.81
END DESCRIPTION:
XS GIS Cut Line= 4
      1620135.58      6855619.67      1620058.55       6855839.9
      1620024.92      6855969.02      1620028.15      6856103.84
#Sta/Elev= 30
  4768.5  1771.7  4809.1 1770.57    4815 1770.88  4862.1 1769.11  4871.8  1769.1
  4893.9 1768.27  4902.9 1767.44  4908.2 1768.54    4915 1768.27  4933.9  1769.2
  4939.2 1767.91  4957.4 1765.24  4964.9 1763.05  4970.2  1763.4  4978.6 1762.34
  5020.5 1762.26    5021 1761.76  5040.5 1761.76    5041 1762.26  5041.2 1765.09
  5051.5 1766.78  5061.9 1769.27  5071.2 1768.99  5076.4 1769.42  5103.2 1768.87
  5123.9 1767.31  5135.2 1767.64  5154.2 1769.28  5194.2 1771.69  5270.1 1772.34
#Mann= 3 ,-1 , 0
  4768.5     .05       0  5020.5     .05       0    5041     .05       0
Bank Sta=5020.5,5041
XS Rating Curve= 0 ,0
Exp/Cntr=0.3,0.1

Type RM Length L Ch R = 1 ,40868   ,261,261,261
BEGIN DESCRIPTION:
Buck Creek 40697.7
END DESCRIPTION:
XS GIS Cut Line= 3
      1619945.49      6855470.33      1619942.89      6855836.92
      1619942.89      6856233.82
#Sta/Elev= 30
  4633.4 1775.22  4711.1 1774.48  4721.1 1773.62  4811.1 1770.43  4821.1 1770.74
  4881.1 1766.94  4891.1 1766.89  4900.8 1764.65  4901.3 1764.15  4920.8 1764.15
  4921.3 1764.65  4931.1 1765.51  4961.1 1765.09  4971.1 1765.96  4991.1 1764.98
  5031.1 1765.86  5051.1 1768.43  5061.1 1769.05  5111.1 1768.65  5121.1 1768.35
  5131.1 1767.06  5141.1 1767.07  5181.1  1769.5  5261.1 1770.31  5271.1 1771.38
  5311.1  1770.8  5351.1 1771.52  5371.1 1771.02  5381.1 1771.78  5396.9 1771.27
#Mann= 3 ,-1 , 0
  4633.4     .05       0  4900.8     .05       0  4921.3     .05       0
Bank Sta=4900.8,4921.3
XS Rating Curve= 0 ,0
Exp/Cntr=0.3,0.1

Type RM Length L Ch R = 1 ,40607   ,226,226,226
BEGIN DESCRIPTION:
Buck Creek 40606.72
END DESCRIPTION:
XS GIS Cut Line= 4
      1619614.75      6855524.96      1619709.81      6855842.72
      1619779.59      6856071.29       1619846.1      6856544.18
#Sta/Elev= 30
  4669.8 1776.54  4688.4 1776.47  4714.7 1774.77  4792.9 1772.51  4798.2 1771.88
  4859.1 1770.97    4913 1767.62  4923.5 1767.57  4930.5 1766.89  4935.7 1767.24
  4954.8 1766.26  4968.8  1764.3  4986.1 1764.67  4996.9 1763.63  4997.4 1763.13
  5016.9 1763.13  5017.4 1763.63    5040 1764.89  5059.3 1767.23  5067.6 1767.51
  5100.4 1766.54  5132.5 1766.54  5138.4 1767.63  5153.4 1767.55    5204 1768.94
  5418.9 1770.28  5560.3  1772.4  5590.6 1773.91  5651.2 1773.47    5718 1774.49
#Mann= 3 ,-1 , 0
  4669.8     .05       0  4996.9     .04       0  5017.4     .05       0
Bank Sta=4996.9,5017.4
XS Rating Curve= 0 ,0
Exp/Cntr=0.3,0.1

Type RM Length L Ch R = 1 ,40381   ,313,313,313
BEGIN DESCRIPTION:
Buck Creek 40380.99
END DESCRIPTION:
XS GIS Cut Line= 4
      1619395.37      6855621.61      1619499.53      6855890.68
      1619557.66      6856060.03      1619611.78      6856914.74
#Sta/Elev= 30
  4713.1 1775.94  4762.8 1774.75  4780.1 1773.65  4827.2 1772.77  4848.6 1771.36
  4864.6 1771.18  4889.1 1768.64    4988 1763.53  5019.9 1763.93  5024.5 1763.27
    5025 1762.77  5044.6 1762.77  5045.1 1763.27  5051.7 1768.03  5060.8 1770.12
  5066.1 1765.93  5072.8 1765.95  5092.1 1767.79  5097.4 1765.28  5136.2 1765.92
    5168 1767.21  5298.9 1768.43  5328.9  1767.9  5459.2 1769.35  5489.3 1769.16
  5688.5 1772.39  5693.5 1771.31    5870 1774.29  5990.3 1774.93  6037.1 1775.78
#Mann= 3 ,-1 , 0
  4713.1     .05       0  5024.5     .03       0  5045.1     .05       0
Bank Sta=5024.5,5045.1
XS Rating Curve= 0 ,0
Exp/Cntr=0.3,0.1

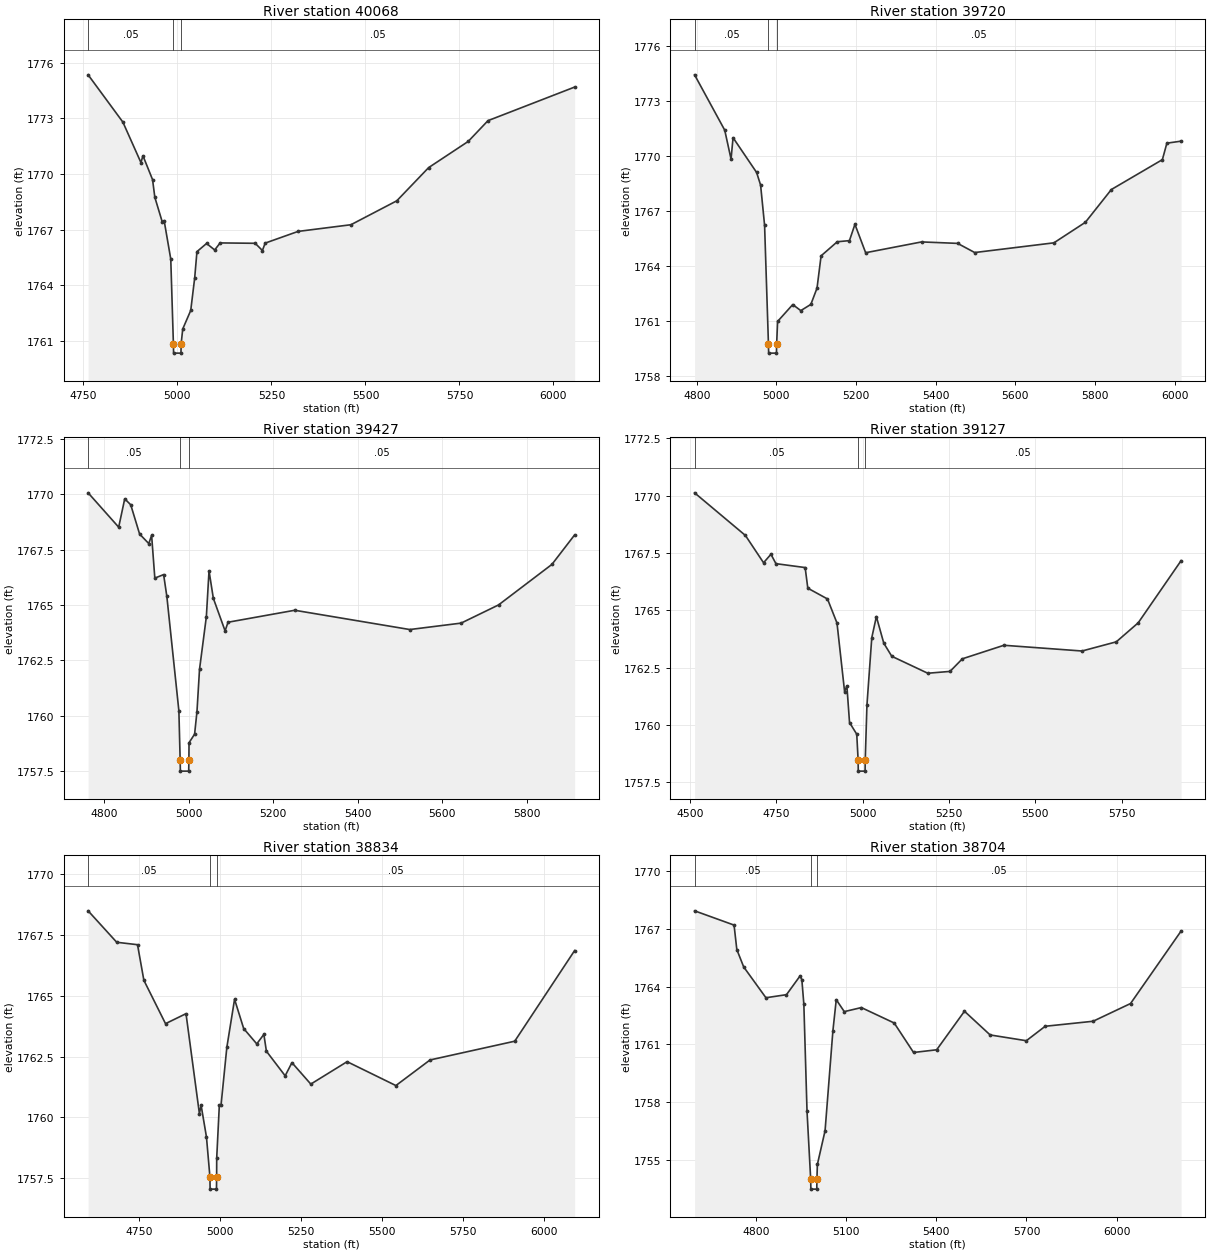
Type RM Length L Ch R = 1 ,40068   ,348,348,348
BEGIN DESCRIPTION:
Buck Creek 40067.63
END DESCRIPTION:
XS GIS Cut Line= 4
      1619122.86      6855720.87      1619202.71      6855945.65
       1619262.5      6856113.54      1619535.93      6856946.87
#Sta/Elev= 30
  4762.5 1775.34    4855 1772.79    4903 1770.61  4908.3 1770.98  4933.9 1769.69
  4939.9 1768.74  4959.4 1767.43  4964.7 1767.48  4982.3 1765.41  4989.3 1760.84
  4989.8 1760.34  5009.4 1760.34  5009.9 1760.84  5014.1 1761.64  5035.4 1762.64
    5046 1764.41  5051.9 1765.81  5077.5 1766.25  5099.1  1765.9  5113.6 1766.28
  5206.8 1766.26    5226 1765.87  5233.4 1766.27  5320.8  1766.9  5461.4 1767.26
  5583.4 1768.55  5668.1 1770.34  5773.3 1771.75  5825.9 1772.87  6056.3 1774.68
#Mann= 3 ,-1 , 0
  4762.5     .05       0  4989.3     .06       0  5009.9     .05       0
Bank Sta=4989.3,5009.9
XS Rating Curve= 0 ,0
Exp/Cntr=0.3,0.1

Type RM Length L Ch R = 1 ,39720   ,293,293,293
BEGIN DESCRIPTION:
Buck Creek 39719.61
END DESCRIPTION:
XS GIS Cut Line= 4
      1618876.15      6855732.32      1618884.83      6855940.62
       1618941.6      6856246.68      1619195.23      6856901.31
#Sta/Elev= 30
  4794.5 1774.44  4870.2 1771.42  4886.1 1769.84  4891.1 1771.01  4950.3 1769.11
  4960.3 1768.42  4970.3 1766.23    4980 1759.75  4980.5 1759.25  5000.1 1759.25
  5000.6 1759.75    5003 1760.98    5041  1761.9  5061.3 1761.57  5086.5 1761.91
    5102  1762.8  5112.2 1764.56  5152.9 1765.33  5183.4 1765.39  5197.2 1766.28
  5224.1 1764.73  5364.6 1765.32  5455.1 1765.24    5498 1764.74  5696.9 1765.27
  5775.9 1766.39  5841.2 1768.18  5969.3 1769.81  5980.6 1770.71  6016.3 1770.82
#Mann= 3 ,-1 , 0
  4794.5     .05       0    4980     .05       0  5000.6     .05       0
Bank Sta=4980,5000.6
XS Rating Curve= 0 ,0
Exp/Cntr=0.3,0.1

Type RM Length L Ch R = 1 ,39427   ,300,300,300
BEGIN DESCRIPTION:
Buck Creek 39427.15
END DESCRIPTION:
XS GIS Cut Line= 4
      1618494.36      6855916.29      1618651.49        6856096.
      1618770.85      6856326.76      1619071.51      6856905.62
#Sta/Elev= 30
    4762 1770.06  4834.3 1768.51  4848.6 1769.79  4862.8 1769.52  4883.8  1768.2
  4905.5 1767.77  4912.2 1768.14  4919.8 1766.21  4940.6 1766.37  4948.2 1765.39
  4976.7 1760.22  4979.7    1758  4980.2  1757.5  4999.9  1757.5  5000.4    1758
  5000.7 1758.78  5013.9 1759.17  5019.5 1760.19  5025.5 1762.09  5041.7 1764.47
    5048 1766.54  5058.2  1765.3    5086 1763.83    5093 1764.22  5250.7 1764.76
  5522.9 1763.89  5644.3 1764.18  5732.8    1765  5859.1 1766.83  5912.8 1768.16
#Mann= 3 ,-1 , 0
    4762     .05       0  4979.7     .05       0  5000.4     .05       0
Bank Sta=4979.7,5000.4
XS Rating Curve= 0 ,0
Exp/Cntr=0.3,0.1

Type RM Length L Ch R = 1 ,39127   ,293,293,293
BEGIN DESCRIPTION:
Buck Creek 39126.69
END DESCRIPTION:
XS GIS Cut Line= 5
      1618116.66      6855853.11      1618232.06      6856046.27
      1618403.53      6856247.78       1618535.6      6856473.73
      1619017.26      6856920.83
#Sta/Elev= 30
  4513.7 1770.12  4660.9 1768.26  4713.4 1767.07  4734.8 1767.44  4749.2 1767.03
  4833.8 1766.86  4841.5 1765.96  4898.5 1765.49    4926 1764.44    4948 1761.45
  4954.6  1761.7  4962.3  1760.1  4983.2 1759.59  4987.1 1758.48  4987.6 1757.98
  5007.3 1757.98  5007.8 1758.48  5012.7 1760.86  5026.7  1763.8    5040 1764.72
  5061.5 1763.56  5084.6 1762.99  5188.8 1762.25  5253.2 1762.33    5289 1762.88
  5409.2 1763.47  5635.4 1763.22  5734.6 1763.62  5798.1 1764.45  5922.2 1767.16
#Mann= 3 ,-1 , 0
  4513.7     .05       0  4987.1     .05       0  5007.8     .05       0
Bank Sta=4987.1,5007.8
XS Rating Curve= 0 ,0
Exp/Cntr=0.3,0.1

Type RM Length L Ch R = 1 ,38834   ,130,130,130
BEGIN DESCRIPTION:
Buck Creek 38833.84
END DESCRIPTION:
XS GIS Cut Line= 6
      1618012.49      6855950.77       1618065.6       6856116.1
       1618138.7      6856338.35      1618177.61      6856478.08
      1618255.56      6856584.47      1618993.37      6856933.84
#Sta/Elev= 30
  4593.9 1768.48  4682.1 1767.19  4746.3 1767.09  4765.9 1765.63  4832.7 1763.85
  4895.9 1764.26  4937.2 1760.16  4942.5  1760.5    4959  1759.2  4969.7 1757.56
  4970.2 1757.06  4989.9 1757.06  4990.4 1757.56  4990.6 1758.33  4998.7  1760.5
  5003.9  1760.5  5021.9 1762.88  5045.7 1764.85  5073.8 1763.65  5114.2 1763.02
  5136.1 1763.41  5143.9 1762.72  5201.8 1761.71  5222.7 1762.25  5280.9 1761.37
  5392.9 1762.29  5543.4 1761.31  5648.7 1762.36    5910 1763.13  6094.8 1766.85
#Mann= 3 ,-1 , 0
  4593.9     .05       0  4969.7     .05       0  4990.4     .05       0
Bank Sta=4969.7,4990.4
XS Rating Curve= 0 ,0
Exp/Cntr=0.3,0.1

Type RM Length L Ch R = 1 ,38704   ,264,264,264
BEGIN DESCRIPTION:
Buck Creek 38704.16
END DESCRIPTION:
XS GIS Cut Line= 6
      1617838.91      6855979.04      1617928.59      6856170.65
      1618010.67      6856344.86       1618060.4      6856497.61
      1618099.31      6856588.81      1618980.21      6856955.49
#Sta/Elev= 30
  4596.2 1767.93  4727.5 1767.19  4736.7 1765.92  4759.5 1765.02  4833.5 1763.42
  4901.9 1763.58  4947.4 1764.56    4953 1764.35  4959.6 1763.09  4970.2 1757.52
  4982.4 1753.99  4982.9 1753.49  5002.6 1753.49  5003.1 1753.99  5004.6 1754.77
  5030.2 1756.52  5056.2  1761.7  5067.4 1763.32  5094.1  1762.7  5150.9 1762.91
  5260.1 1762.11  5324.5 1760.58  5401.4 1760.72  5493.8 1762.72  5579.2 1761.49
  5699.6 1761.19  5762.3 1761.94  5921.6  1762.2  6046.2 1763.12  6214.3 1766.88
#Mann= 3 ,-1 , 0
  4596.2     .05       0  4982.4     .05       0  5003.1     .05       0
Bank Sta=4982.4,5003.1
XS Rating Curve= 0 ,0
Exp/Cntr=0.3,0.1

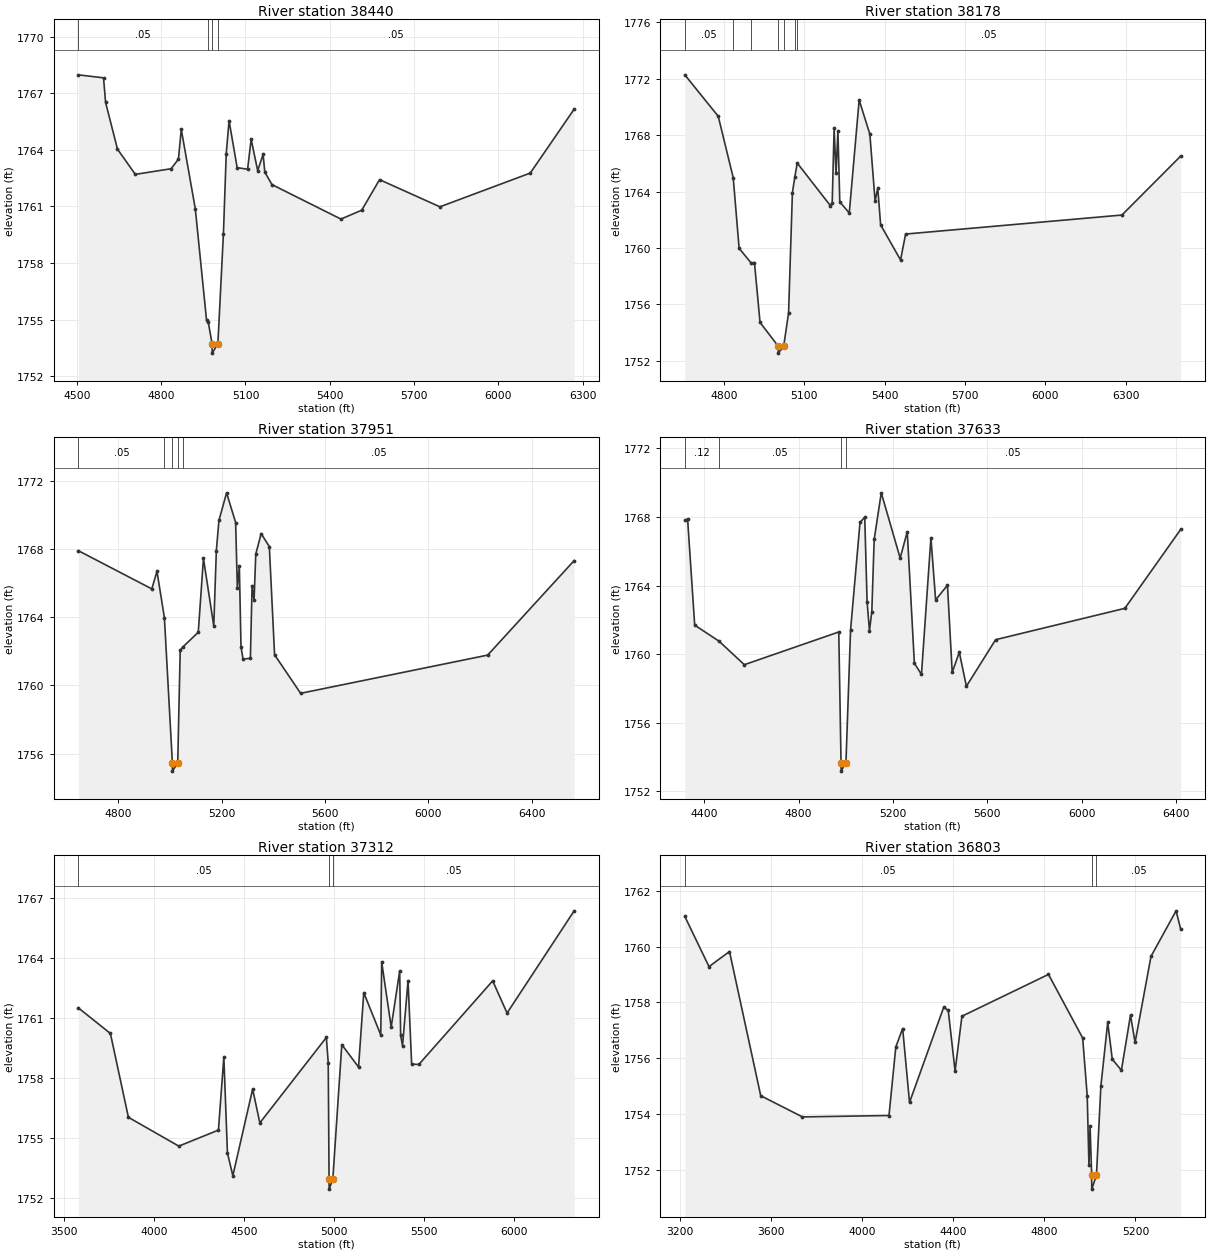
Type RM Length L Ch R = 1 ,38440   ,262,262,262
BEGIN DESCRIPTION:
Mapping XS 8bdfb8ee
END DESCRIPTION:
XS GIS Cut Line= 4
       1617747.2      6856000.78      1617823.15      6856321.94
      1617821.76      6856560.61      1618945.65       6856966.4
#Sta/Elev= 30
  4505.6 1767.98  4595.2 1767.82  4602.5 1766.52  4644.8 1764.04  4708.3  1762.7
  4835.6    1763  4861.7 1763.51  4871.7 1765.09  4921.7 1760.87  4961.7 1754.96
  4967.5 1754.88  4981.3 1753.72  4981.8 1753.22    5002 1753.72  5021.7 1759.56
  5031.7  1763.8  5041.7 1765.55  5070.5 1763.06  5107.6 1762.97  5120.3 1764.56
  5143.5  1762.9  5162.8 1763.76  5168.9 1762.82  5194.2 1762.16  5439.6 1760.33
  5513.6  1760.8    5577 1762.42  5791.7 1760.98  6113.1 1762.77  6269.2 1766.16
#Mann= 4 ,-1 , 0
  4505.6     .05       0  4967.5     .12       0  4981.3     .05       0
    5002     .05       0
Bank Sta=4981.3,5002
XS Rating Curve= 0 ,0
Exp/Cntr=0.3,0.1

Type RM Length L Ch R = 1 ,38178   ,227,227,227
BEGIN DESCRIPTION:
Mapping XS 1f567a0c
END DESCRIPTION:
XS GIS Cut Line= 4
      1617360.89      6856196.04      1617647.37      6856536.79
        1617777.      6856668.07      1618956.55      6856985.95
#Sta/Elev= 30
  4654.1 1772.28  4778.9 1769.34  4834.9 1764.98  4856.9 1759.97  4901.7 1758.93
  4914.2 1758.96    4935 1754.71  5002.7 1753.03  5003.2 1752.53  5023.4 1753.03
  5041.6 1755.38  5055.9 1763.92  5064.9 1765.02  5073.9 1766.02  5197.5    1763
  5204.5 1763.18  5211.6 1768.48  5218.7 1765.31  5225.8 1768.28  5232.8 1763.26
  5268.2 1762.48  5305.1 1770.49  5345.1 1768.07  5364.6 1763.32  5374.6 1764.24
  5385.3 1761.63  5459.7 1759.14  5478.5 1760.98  6286.3 1762.33  6505.4 1766.51
#Mann= 7 ,-1 , 0
  4654.1     .05       0  4834.9     .12       0  4901.7     .05       0
  5002.7     .05       0  5023.4     .05       0  5064.9     .12       0
  5073.9     .05       0
Bank Sta=5002.7,5023.4
XS Rating Curve= 0 ,0
Exp/Cntr=0.3,0.1

Type RM Length L Ch R = 1 ,37951   ,318,318,318
BEGIN DESCRIPTION:
Mapping XS af056cd9
END DESCRIPTION:
XS GIS Cut Line= 4
      1617150.43      6856651.81       1617703.8      6856660.49
      1617821.53      6856799.31      1618986.93      6857014.16
#Sta/Elev= 30
  4644.6 1767.89  4929.2 1765.65  4949.2 1766.68    4978 1763.96  5008.8 1755.47
  5009.3 1754.97  5029.6 1755.47  5039.2 1762.05  5049.1 1762.24  5109.2 1763.11
  5129.2 1767.44  5169.2 1763.48  5179.2  1767.9  5189.2 1769.66  5218.8 1771.28
  5253.9 1769.54  5260.5 1765.72  5268.2 1766.99  5274.7 1762.25  5282.5 1761.54
    5311 1761.58  5317.6 1765.84  5325.3 1764.99  5331.9 1767.69  5352.7 1768.89
  5384.4 1768.13  5404.7 1761.79  5505.6 1759.53  6230.2 1761.77  6565.1 1767.31
#Mann= 5 ,-1 , 0
  4644.6     .05       0    4978     .12       0  5008.8     .07       0
  5029.6     .12       0  5049.1     .05       0
Bank Sta=5008.8,5029.6
XS Rating Curve= 0 ,0
Exp/Cntr=0.3,0.1

Type RM Length L Ch R = 1 ,37633   ,321,321,321
BEGIN DESCRIPTION:
Buck Creek 37633.59
END DESCRIPTION:
XS GIS Cut Line= 5
      1616873.16      6856977.26      1617255.14      6856958.23
      1617552.08       6856959.7       1617743.4      6856955.56
      1618970.89      6857031.46
#Sta/Elev= 30
    4318  1767.8  4329.9 1767.88  4359.9 1761.69  4463.3 1760.75  4570.2 1759.38
  4970.3 1761.29  4979.9 1753.67  4980.4 1753.17  5000.7 1753.67  5020.3 1761.41
  5060.3 1767.68  5080.3 1767.99  5090.3 1763.06  5100.3 1761.36  5110.3 1762.48
  5120.3 1766.69  5150.4 1769.41  5230.4  1765.6  5260.5 1767.14  5290.6 1759.47
  5320.6 1758.81  5360.7 1766.78  5380.7 1763.16  5430.8 1764.02  5450.9 1758.93
  5480.9 1760.11    5511 1758.12  5634.8 1760.84  6182.3 1762.67  6418.6 1767.27
#Mann= 4 ,-1 , 0
    4318     .12       0  4463.3     .05       0  4979.9     .05       0
  5000.7     .05       0
Bank Sta=4979.9,5000.7
XS Rating Curve= 0 ,0
Exp/Cntr=0.3,0.1

Type RM Length L Ch R = 1 ,37312   ,509,509,509
BEGIN DESCRIPTION:
Buck Creek 37312.44
END DESCRIPTION:
XS GIS Cut Line= 5
      1616206.91      6857330.99      1617425.48      6857314.52
      1617612.85       6857247.9      1617972.26      6857093.87
      1618917.48      6857113.98
#Sta/Elev= 30
  3579.3 1761.52  3757.4 1760.24  3857.4 1756.05  4137.4 1754.61  4357.5 1755.41
  4387.5 1759.06  4407.5 1754.27  4437.5 1753.13  4547.5 1757.46  4587.5 1755.77
  4956.9 1760.04  4967.3 1758.78    4972 1752.96  4972.5 1752.46  4992.8 1752.96
  5042.7 1759.68  5135.7 1758.56  5164.7 1762.28    5259 1760.17  5264.4  1763.8
    5317 1760.56  5364.2 1763.36  5369.6 1760.14    5380 1759.62  5410.6 1762.88
  5430.6 1758.71  5470.6 1758.69  5880.7 1762.87  5960.7 1761.26  6333.3 1766.37
#Mann= 3 ,-1 , 0
  3579.3     .05       0    4972     .05       0  4992.8     .05       0
Bank Sta=4972,4992.8
XS Rating Curve= 0 ,0
Exp/Cntr=0.3,0.1

Type RM Length L Ch R = 1 ,36803   ,147,147,147
BEGIN DESCRIPTION:
Buck Creek 36803.25
END DESCRIPTION:
XS GIS Cut Line= 4
      1616128.83       6857439.5      1617496.01        6857413.
      1617905.14        6857413.      1618304.92      6857406.49
#Sta/Elev= 30
  3221.7 1761.08  3327.9 1759.28  3417.9 1759.82    3555 1754.65    3738 1753.89
    4118 1753.94    4148  1756.4    4178 1757.06  4208.1 1754.41  4358.1 1757.82
  4378.1 1757.71  4408.1 1755.53  4438.1  1757.5  4818.1    1759  4968.1 1756.72
  4988.1 1754.65  4995.7 1752.16  5000.7 1753.56  5007.6  1751.8  5008.1  1751.3
  5028.7  1751.8  5048.1    1755  5078.1 1757.28  5098.1 1755.96  5138.1 1755.56
  5178.1 1757.54  5198.2 1756.56  5268.2 1759.65  5378.2 1761.28  5398.1 1760.63
#Mann= 3 ,-1 , 0
  3221.7     .05       0  5007.6     .03       0  5028.7     .05       0
Bank Sta=5007.6,5028.7
XS Rating Curve= 0 ,0
Exp/Cntr=0.3,0.1

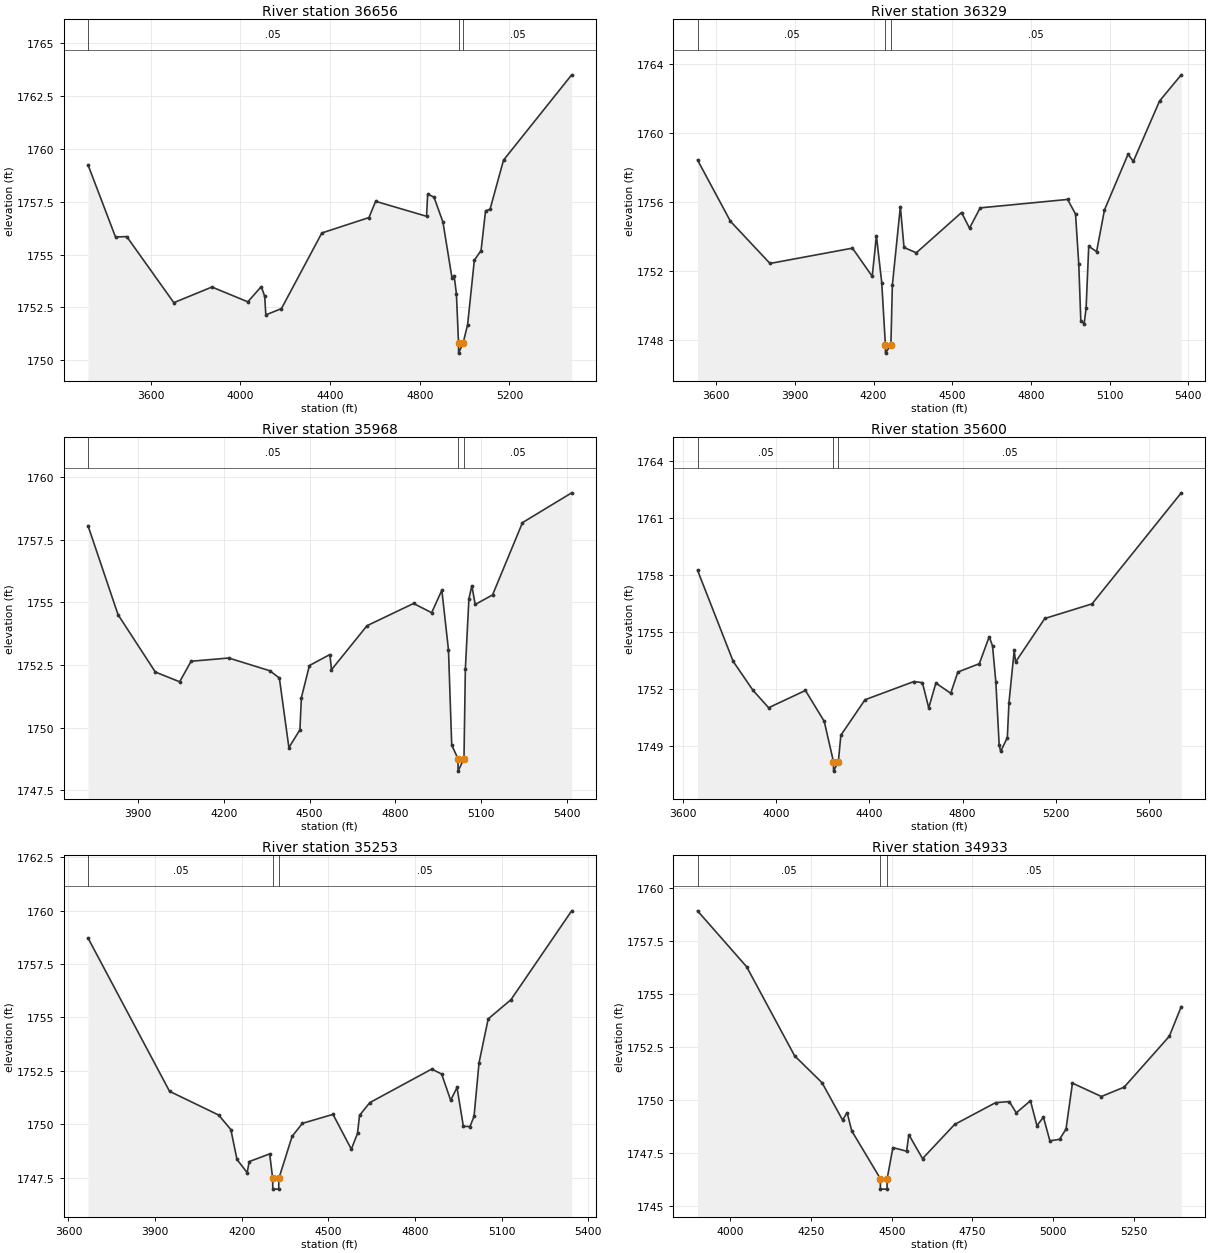
Type RM Length L Ch R = 1 ,36656   ,327,327,327
BEGIN DESCRIPTION:
Buck Creek 36656.33
END DESCRIPTION:
XS GIS Cut Line= 4
      1616172.23      6857515.45      1617537.24      6857545.84
      1617852.41      6857539.74      1618328.78      6857558.18
#Sta/Elev= 30
  3320.1 1759.25  3442.9 1755.83  3492.9 1755.85    3703 1752.72    3873 1753.46
    4033 1752.76  4093.1 1753.48  4108.3 1753.02  4113.3 1752.14  4183.1 1752.44
  4363.1 1756.02  4573.2 1756.75  4603.2 1757.52  4830.2 1756.81  4835.2 1757.86
  4863.2 1757.72  4903.2 1756.54  4943.3 1753.91  4953.3    1754  4963.3 1753.14
  4972.7 1750.83  4973.2 1750.33  4993.8 1750.83  5013.3 1751.68  5043.3 1754.73
  5073.3 1755.19  5093.3 1757.07  5113.3 1757.14  5173.4 1759.47  5477.4 1763.51
#Mann= 3 ,-1 , 0
  3320.1     .05       0  4972.7     .05       0  4993.8     .05       0
Bank Sta=4972.7,4993.8
XS Rating Curve= 0 ,0
Exp/Cntr=0.3,0.1

Type RM Length L Ch R = 1 ,36329   ,361,361,361
BEGIN DESCRIPTION:
Buck Creek 36329.24
END DESCRIPTION:
XS GIS Cut Line= 4
      1616202.61      6857532.82      1617283.73      6857714.38
      1617655.14      6857765.87      1618027.56      6857772.38
#Sta/Elev= 30
  3528.9 1758.43  3654.4 1754.87  3805.1 1752.42  4119.4 1753.31  4194.8 1751.67
  4210.7 1754.03    4231 1751.31  4244.9 1747.71  4245.4 1747.21    4266 1747.71
  4271.5 1751.16    4302 1755.72    4316 1753.35  4362.8 1753.04  4535.2 1755.38
  4565.6 1754.47  4606.2 1755.65  4939.4 1756.14  4969.7 1755.29    4982 1752.39
  4989.9 1749.08  5002.6 1748.92    5010 1749.82    5020 1753.42    5050 1753.11
    5080 1755.53    5170 1758.77    5190 1758.35    5290 1761.86  5372.6 1763.38
#Mann= 3 ,-1 , 0
  3528.9     .05       0  4244.9     .05       0    4266     .05       0
Bank Sta=4244.9,4266
XS Rating Curve= 0 ,0
Exp/Cntr=0.3,0.1

Type RM Length L Ch R = 1 ,35968   ,368,368,368
BEGIN DESCRIPTION:
Buck Creek 35967.77
END DESCRIPTION:
XS GIS Cut Line= 4
      1616209.16      6857563.21      1617196.83      6857854.77
      1617396.03      6857998.94      1617764.48      6858191.63
#Sta/Elev= 30
  3725.1 1758.07  3830.3 1754.51  3960.6 1752.22  4045.7 1751.83  4085.7 1752.65
  4217.4 1752.78  4361.1 1752.27  4394.4 1751.98  4427.7  1749.2  4466.2 1749.91
  4471.5  1751.2  4499.5 1752.48  4571.3 1752.92  4576.5 1752.31  4700.9 1754.07
  4863.7 1754.96    4927 1754.59  4962.6 1755.49  4985.8  1753.1  4997.1  1749.3
  5018.9 1748.76  5019.4 1748.26    5040 1748.76  5044.8 1752.33  5057.2 1755.14
  5067.4 1755.67  5079.3 1754.92  5139.9  1755.3  5244.6 1758.19  5416.6 1759.38
#Mann= 3 ,-1 , 0
  3725.1     .05       0  5018.9     .05       0    5040     .05       0
Bank Sta=5018.9,5040
XS Rating Curve= 0 ,0
Exp/Cntr=0.3,0.1

Type RM Length L Ch R = 1 ,35600   ,347,347,347
BEGIN DESCRIPTION:
Buck Creek 35600.21
END DESCRIPTION:
XS GIS Cut Line= 5
      1616183.03      6857600.06       1617156.3      6858206.85
      1617304.23      6858331.73      1617584.22      6858504.49
      1617921.53      6858734.88
#Sta/Elev= 30
  3661.6 1758.26  3814.8 1753.46  3899.7 1751.94    3967 1751.02  4125.1 1751.93
    4206  1750.3  4245.5 1748.18    4246 1747.68  4266.6 1748.18  4277.3 1749.57
  4381.1 1751.44  4591.2  1752.4  4627.7 1752.34  4654.9 1751.01  4685.5 1752.32
  4749.3 1751.78  4779.9  1752.9  4872.3 1753.34  4914.6 1754.76  4928.9 1754.28
  4943.2 1752.37  4957.5 1749.05    4964 1748.72  4992.6 1749.45  4999.4 1751.27
  5022.1 1754.04    5028 1753.43  5153.4 1755.72  5356.3 1756.49  5739.6 1762.34
#Mann= 3 ,-1 , 0
  3661.6     .05       0  4245.5     .03       0  4266.6     .05       0
Bank Sta=4245.5,4266.6
XS Rating Curve= 0 ,0
Exp/Cntr=0.3,0.1

Type RM Length L Ch R = 1 ,35253   ,320,320,320
BEGIN DESCRIPTION:
Buck Creek 35252.61
END DESCRIPTION:
XS GIS Cut Line= 4
      1616155.73      6857617.89       1617013.9      6858430.15
      1617077.67      6858571.86      1617190.25      6858890.55
#Sta/Elev= 30
  3667.5 1758.72    3950 1751.54  4119.9 1750.43  4162.2 1749.75  4183.5 1748.35
  4218.7 1747.73  4225.9 1748.25  4296.7 1748.61  4307.1 1747.46  4307.6 1746.96
    4328 1746.96  4328.5 1747.46  4374.4 1749.43    4410 1750.04    4516 1750.46
  4579.5 1748.83  4600.9 1749.57  4607.8 1750.41  4643.4 1751.01  4857.7 1752.58
  4892.2 1752.35  4923.5 1751.12  4945.5 1751.72  4967.4  1749.9  4990.3 1749.89
  5004.5 1750.37  5021.6 1752.87  5053.4 1754.93  5132.3 1755.83  5342.5 1759.99
#Mann= 3 ,-1 , 0
  3667.5     .05       0  4307.1     .05       0  4328.5     .05       0
Bank Sta=4307.1,4328.5
XS Rating Curve= 0 ,0
Exp/Cntr=0.3,0.1

Type RM Length L Ch R = 1 ,34933   ,486,486,486
BEGIN DESCRIPTION:
Buck Creek 34933.33
END DESCRIPTION:
XS GIS Cut Line= 5
      1616096.68       6857701.2      1616555.52       6858197.8
      1616773.23      6858433.42      1616778.01      6858541.13
       1616783.2      6858934.96
#Sta/Elev= 30
  3898.2 1758.91  4050.4 1756.27    4199 1752.07    4284  1750.8  4347.6 1749.04
  4361.7 1749.39  4375.9 1748.53  4464.4 1746.28  4464.9 1745.78  4485.3 1745.78
  4485.8 1746.28  4503.5 1747.74    4546 1747.57  4552.8 1748.35  4595.3 1747.22
  4694.6 1748.83  4821.6 1749.86  4864.1 1749.91  4885.7 1749.38  4929.7 1749.95
  4949.8 1748.77  4969.8 1749.18  4989.8 1748.06  5019.8 1748.13  5039.8 1748.61
  5059.8 1750.78  5149.4 1750.15  5219.8 1750.59  5359.8 1752.99  5396.8 1754.39
#Mann= 3 ,-1 , 0
  3898.2     .05       0  4464.4     .05       0  4485.8     .05       0
Bank Sta=4464.4,4485.8
XS Rating Curve= 0 ,0
Exp/Cntr=0.3,0.1