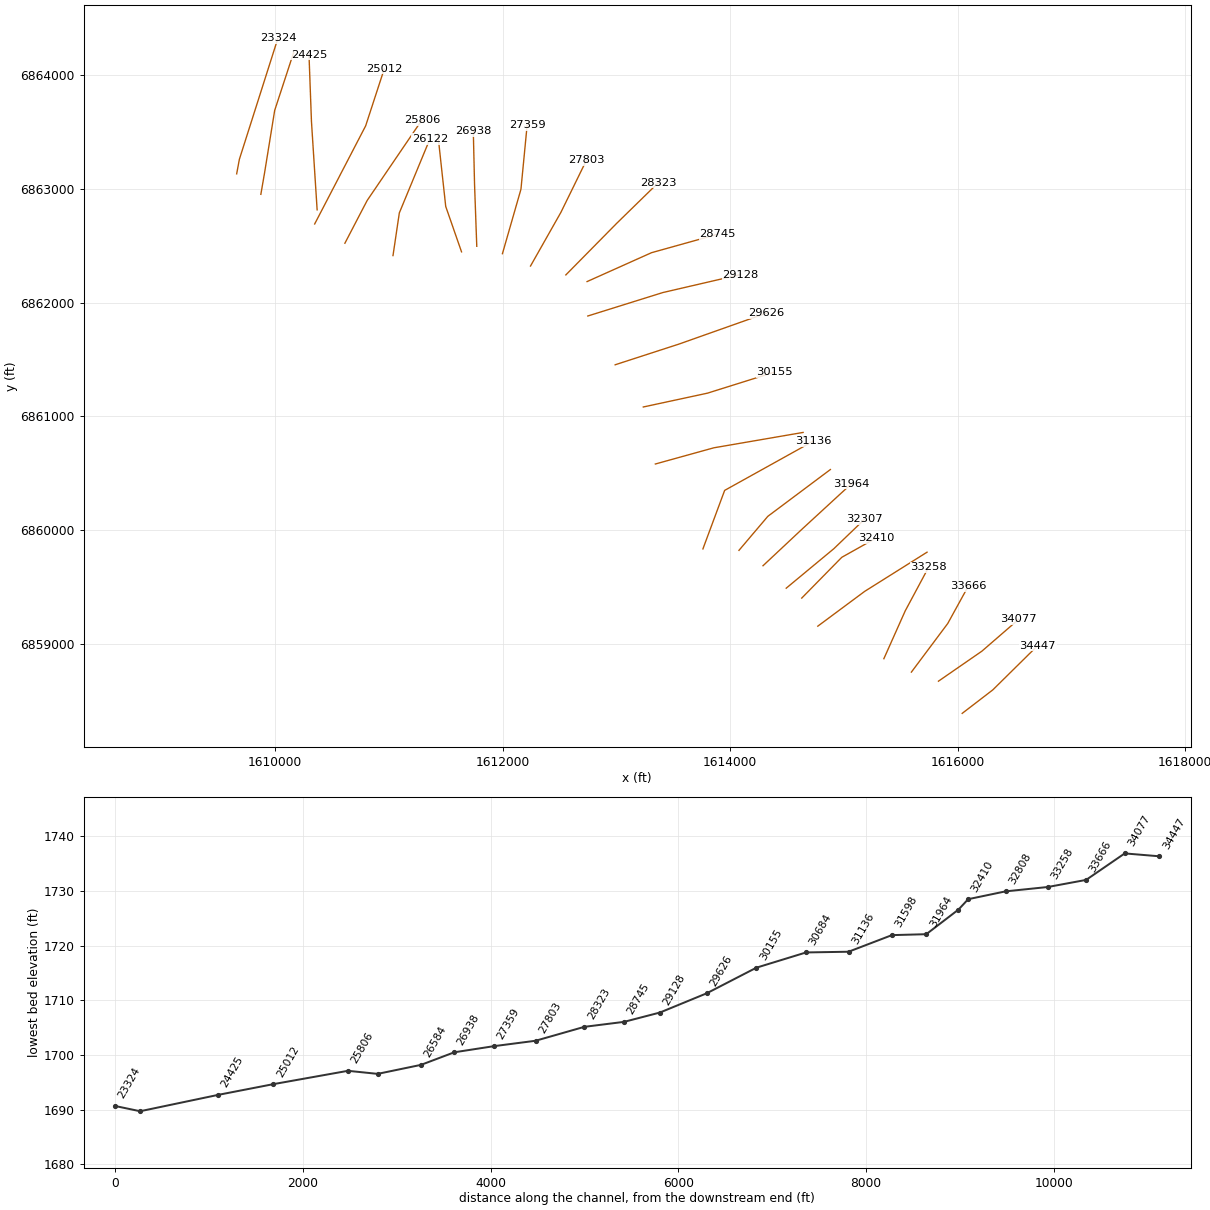
HEC-RAS study Buck Creek.prj: Buck Creek Base Level Engineering

--- Buck Creek.g01 (geometry) --- (continued)

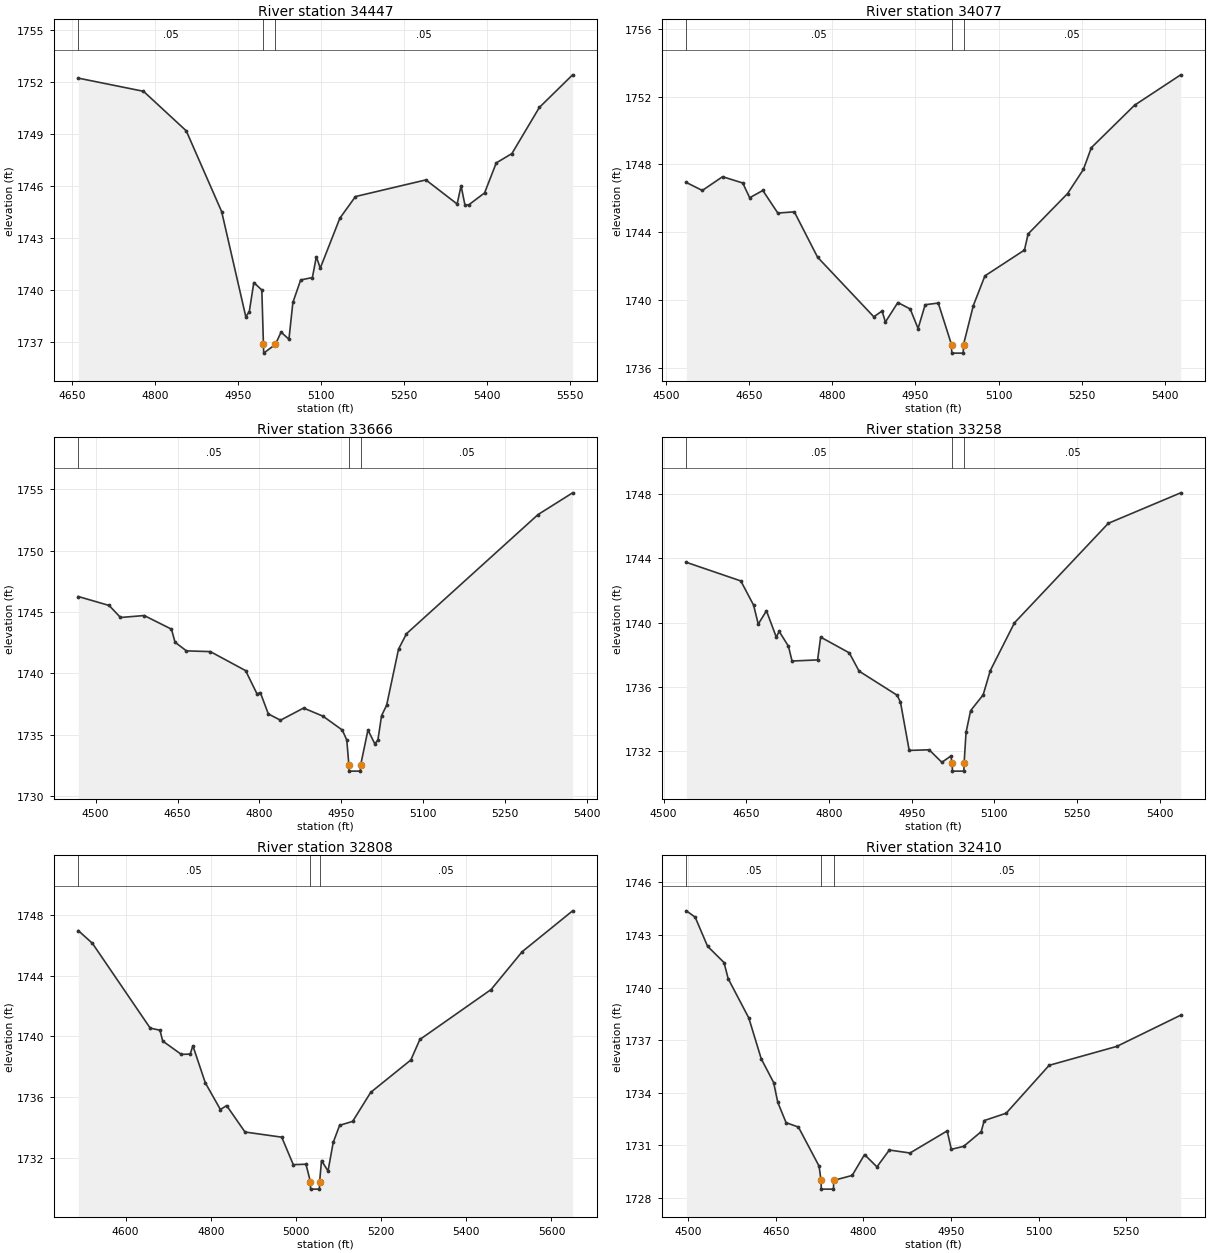
Type RM Length L Ch R = 1 ,34447   ,370,370,370
BEGIN DESCRIPTION:
Buck Creek 34447.11
END DESCRIPTION:
XS GIS Cut Line= 3
      1616040.19      6858388.37      1616309.26      6858594.95
      1616703.78      6858984.28
#Sta/Elev= 30
    4661 1752.22  4778.9 1751.46  4856.2 1749.18  4920.2 1744.52  4963.8 1738.46
  4970.1 1738.75  4978.3 1740.43  4992.8    1740  4995.7 1736.86  4996.2 1736.36
  5017.2 1736.86  5027.6 1737.57  5041.8 1737.16  5048.9 1739.28    5063 1740.58
  5084.2 1740.72  5091.3 1741.92  5098.4 1741.26  5133.8 1744.14    5162 1745.39
  5289.3 1746.35  5345.8 1744.96  5352.9 1746.01    5360 1744.89  5367.1 1744.92
  5395.4  1745.6  5416.5 1747.33  5444.8 1747.87  5494.4 1750.53  5554.5 1752.41
#Mann= 3 ,-1 , 0
    4661     .05       0  4995.7     .05       0  5017.2     .05       0
Bank Sta=4995.7,5017.2
XS Rating Curve= 0 ,0
Exp/Cntr=0.3,0.1

Type RM Length L Ch R = 1 ,34077   ,411,411,411
BEGIN DESCRIPTION:
Buck Creek 34077.02
END DESCRIPTION:
XS GIS Cut Line= 3
      1615831.29      6858671.32      1616213.26      6858935.22
      1616536.14      6859214.71
#Sta/Elev= 30
    4537 1746.94  4565.8 1746.47  4602.3 1747.28  4638.7 1746.91  4651.2 1746.04
  4674.9 1746.47  4701.9 1745.14  4731.7 1745.21  4773.6 1742.54    4875 1739.03
  4889.9 1739.37  4895.9 1738.72  4918.3 1739.87  4940.6 1739.49  4954.8 1738.34
  4967.6 1739.74  4991.2 1739.84  5015.1 1737.39  5015.6 1736.89  5036.2 1736.89
  5036.7 1737.39  5054.4 1739.69  5075.3 1741.44  5146.6 1742.96  5153.2 1743.91
  5224.4 1746.29  5252.9 1747.71  5267.2 1748.99  5345.1 1751.49  5428.3 1753.28
#Mann= 3 ,-1 , 0
    4537     .05       0  5015.1     .03       0  5036.7     .05       0
Bank Sta=5015.1,5036.7
XS Rating Curve= 0 ,0
Exp/Cntr=0.3,0.1

Type RM Length L Ch R = 1 ,33666   ,408,408,408
BEGIN DESCRIPTION:
Buck Creek 33665.92
END DESCRIPTION:
XS GIS Cut Line= 3
      1615593.48      6858751.22      1615912.91      6859178.28
      1616092.54      6859504.72
#Sta/Elev= 30
  4468.1 1746.27  4524.7 1745.54  4545.5 1744.56    4589 1744.72  4638.9 1743.61
  4645.5 1742.54  4666.4 1741.84  4710.2 1741.78  4774.8 1740.23  4795.6 1738.34
  4801.8 1738.44  4816.4  1736.7  4838.7 1736.19    4881 1737.18  4916.5 1736.52
  4951.9 1735.39  4960.2 1734.57    4964 1732.54  4964.5 1732.04  4985.1 1732.04
  4985.6 1732.54    4999 1735.39  5011.5 1734.27  5017.2 1734.57  5023.9 1736.56
  5033.2 1737.41    5055 1741.98  5069.6 1743.24  5310.7 1752.95    5374 1754.72
#Mann= 3 ,-1 , 0
  4468.1     .05       0    4964     .05       0  4985.6     .05       0
Bank Sta=4964,4985.6
XS Rating Curve= 0 ,0
Exp/Cntr=0.3,0.1

Type RM Length L Ch R = 1 ,33258   ,450,450,450
BEGIN DESCRIPTION:
Buck Creek 33258.35
END DESCRIPTION:
XS GIS Cut Line= 3
      1615351.45      6858868.89      1615538.95      6859289.04
      1615745.18      6859673.77
#Sta/Elev= 30
  4541.3 1743.75  4640.1 1742.59  4663.3 1741.08  4671.7  1739.9  4686.6 1740.73
  4704.3  1739.1  4709.8 1739.44  4726.5 1738.52    4733  1737.6  4779.4 1737.67
  4784.9 1739.09  4836.8 1738.11  4854.6 1736.97  4923.6 1735.47  4929.7 1735.03
  4945.5 1732.03  4981.6 1732.07  5004.7 1731.29    5021 1731.68  5023.4 1731.24
  5023.9 1730.74  5044.6 1730.74  5045.1 1731.24  5048.6 1733.16  5056.9 1734.51
  5079.6 1735.49  5092.5    1737  5136.4 1739.98  5306.6 1746.18  5437.9 1748.08
#Mann= 3 ,-1 , 0
  4541.3     .05       0  5023.4     .05       0  5045.1     .05       0
Bank Sta=5023.4,5045.1
XS Rating Curve= 0 ,0
Exp/Cntr=0.3,0.1

Type RM Length L Ch R = 1 ,32808   ,398,398,398
BEGIN DESCRIPTION:
Buck Creek 32808.26
END DESCRIPTION:
XS GIS Cut Line= 3
      1614770.62      6859155.09      1615182.96      6859461.09
      1615731.03      6859805.53
#Sta/Elev= 30
  4488.8 1746.96  4522.1 1746.12  4657.7 1740.54  4680.7  1740.4    4687 1739.69
  4730.8 1738.81  4751.7 1738.83  4757.9 1739.38  4787.1 1736.94  4822.6 1735.18
  4837.2 1735.44  4880.3  1733.7  4966.6 1733.36  4993.7 1731.55  5023.5 1731.58
  5033.8 1730.44  5034.3 1729.94  5055.1 1729.94  5055.6 1730.44    5060 1731.82
  5075.3 1731.13  5087.4 1733.01  5102.5 1734.14  5133.1  1734.4  5175.5 1736.31
  5269.7 1738.44  5290.9 1739.79  5458.2 1743.08  5531.2 1745.57  5649.6 1748.26
#Mann= 3 ,-1 , 0
  4488.8     .05       0  5033.8     .05       0  5055.6     .05       0
Bank Sta=5033.8,5055.6
XS Rating Curve= 0 ,0
Exp/Cntr=0.3,0.1

Type RM Length L Ch R = 1 ,32410   ,103,103,103
BEGIN DESCRIPTION:
Buck Creek 32410.42
END DESCRIPTION:
XS GIS Cut Line= 3
      1614629.56      6859402.12      1614981.14      6859760.21
      1615281.37      6859928.69
#Sta/Elev= 30
  4496.9 1744.38    4512 1744.02  4533.2 1742.36  4561.4 1741.43  4568.5 1740.51
  4603.8 1738.27  4625.1 1735.94  4646.3 1734.59  4653.4 1733.46  4667.6  1732.3
  4688.7 1732.05  4724.1 1729.82  4727.4 1729.01  4727.9 1728.51  4748.7 1728.51
  4749.2 1729.01  4780.7 1729.29  4801.9 1730.48  4823.1 1729.78  4844.3 1730.74
  4879.7 1730.57  4943.3 1731.83  4950.4 1730.78  4971.6 1730.95  5001.6 1731.79
  5006.7 1732.42  5044.3 1732.84  5117.8 1735.57  5233.7 1736.65    5343 1738.43
#Mann= 3 ,-1 , 0
  4496.9     .05       0  4727.4     .03       0  4749.2     .05       0
Bank Sta=4727.4,4749.2
XS Rating Curve= 0 ,0
Exp/Cntr=0.3,0.1

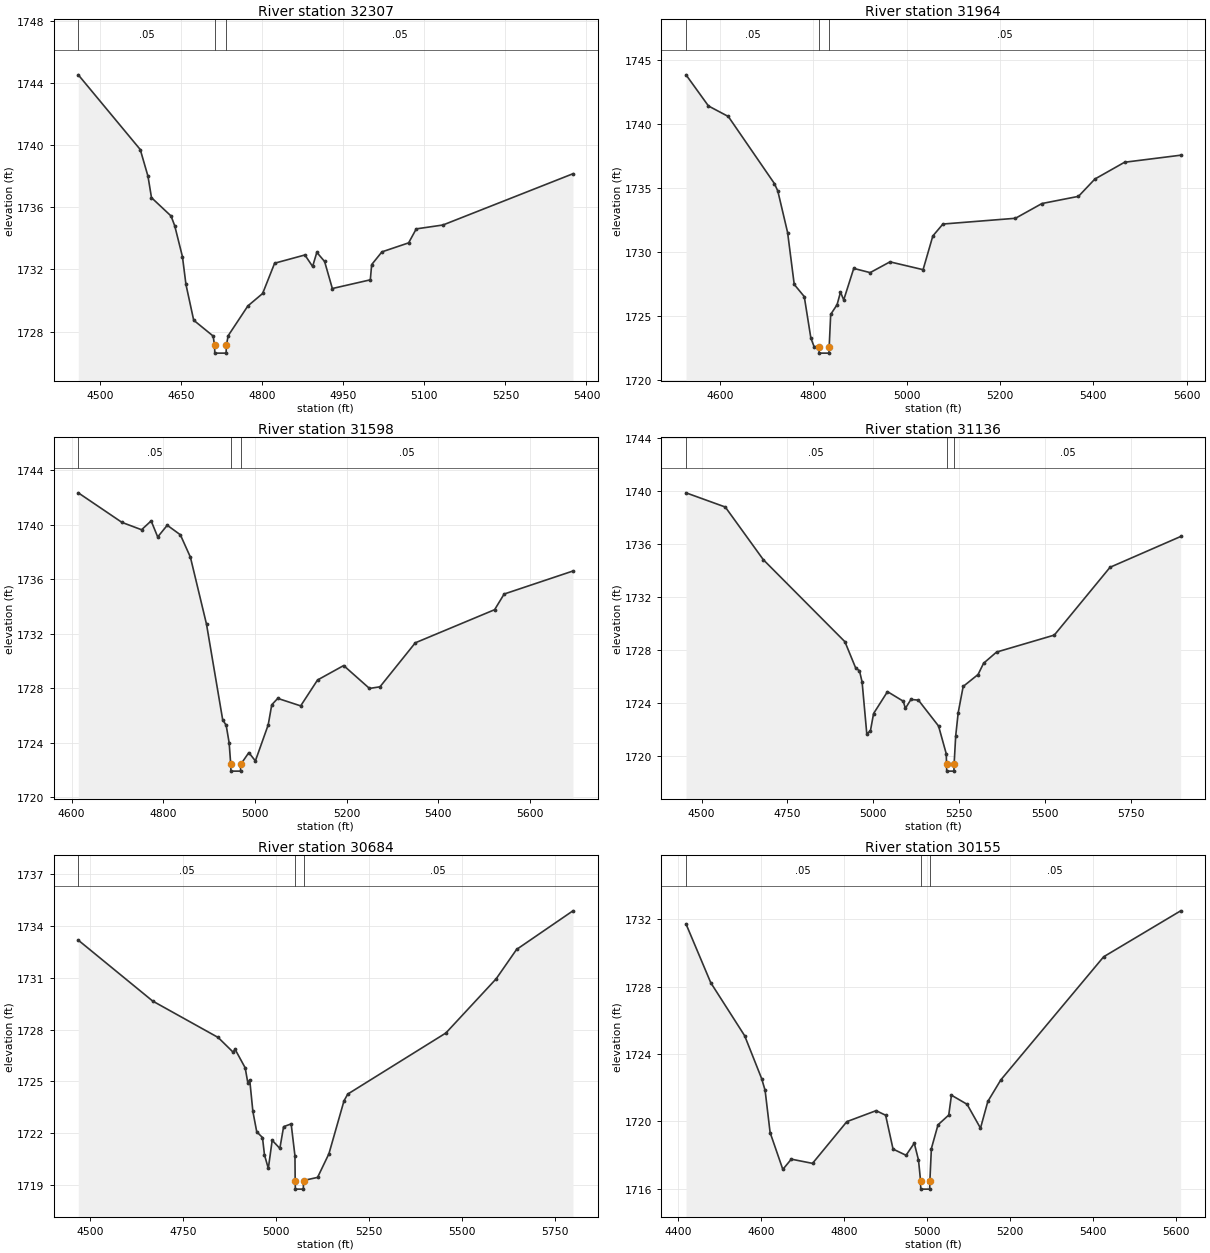
Type RM Length L Ch R = 1 ,32307   ,343,343,343
BEGIN DESCRIPTION:
Buck Creek 32306.93
END DESCRIPTION:
XS GIS Cut Line= 3
      1614492.83      6859488.92      1614911.69      6859836.16
      1615179.67      6860093.33
#Sta/Elev= 30
  4459.5 1744.53  4574.2 1739.72  4588.5    1738    4595 1736.62  4631.2 1735.44
    4638 1734.81  4652.3 1732.82  4658.8 1731.03  4673.1 1728.73  4709.1 1727.71
  4711.7 1727.11  4712.2 1726.61  4733.1 1726.61  4733.6 1727.11  4736.9 1727.73
  4773.4 1729.65  4800.7 1730.45  4822.9  1732.4  4878.9 1732.93  4893.2 1732.19
    4901  1733.1  4915.4 1732.51  4929.7 1730.77    5000 1731.33  5002.5 1732.31
  5021.5 1733.13  5070.9 1733.71    5085 1734.61  5134.4 1734.86    5375 1738.16
#Mann= 3 ,-1 , 0
  4459.5     .05       0  4711.7     .03       0  4733.6     .05       0
Bank Sta=4711.7,4733.6
XS Rating Curve= 0 ,0
Exp/Cntr=0.3,0.1

Type RM Length L Ch R = 1 ,31964   ,366,366,366
BEGIN DESCRIPTION:
Buck Creek 31963.69
END DESCRIPTION:
XS GIS Cut Line= 3
      1614288.85      6859686.41      1614633.92      6860009.78
      1615065.77      6860406.91
#Sta/Elev= 30
  4527.5 1743.81  4575.6 1741.38  4618.1 1740.56  4716.8 1735.33  4724.1 1734.75
  4745.1 1731.51  4759.3 1727.46  4780.8 1726.51  4794.9 1723.28  4801.8 1722.61
  4812.3  1722.6  4812.8  1722.1  4833.7  1722.1  4834.2  1722.6  4837.4 1725.12
  4851.1 1725.88  4858.4 1726.86  4865.3 1726.25  4886.8 1728.71  4921.9 1728.38
  4964.4 1729.22  5035.3 1728.61  5056.2 1731.24  5077.8 1732.17  5233.2 1732.62
  5289.9 1733.77  5368.2 1734.33  5403.3 1735.68  5466.9 1736.99  5587.1 1737.54
#Mann= 3 ,-1 , 0
  4527.5     .05       0  4812.3     .05       0  4834.2     .05       0
Bank Sta=4812.3,4834.2
XS Rating Curve= 0 ,0
Exp/Cntr=0.3,0.1

Type RM Length L Ch R = 1 ,31598   ,462,462,462
BEGIN DESCRIPTION:
Buck Creek 31598.15
END DESCRIPTION:
XS GIS Cut Line= 3
      1614077.48      6859821.39       1614331.4      6860120.89
      1614881.16      6860532.13
#Sta/Elev= 30
  4614.5 1742.36  4709.8 1740.19  4752.6 1739.65  4773.5  1740.3  4787.8 1739.12
  4808.6 1739.98  4837.2 1739.28  4859.1 1737.64  4894.3 1732.71  4929.5 1725.71
  4937.2 1725.29  4943.7    1724  4947.1 1722.43  4947.6 1721.93  4968.5 1721.93
    4969 1722.43  4986.6 1723.29  5000.9 1722.68  5028.9 1725.33  5036.6  1726.8
  5049.7 1727.27  5099.7 1726.72  5136.5 1728.62  5193.5 1729.68  5249.8    1728
  5272.7 1728.12  5349.8 1731.35  5522.8 1733.78  5543.6 1734.93  5693.7 1736.62
#Mann= 3 ,-1 , 0
  4614.5     .05       0  4947.1     .05       0    4969     .05       0
Bank Sta=4947.1,4969
XS Rating Curve= 0 ,0
Exp/Cntr=0.3,0.1

Type RM Length L Ch R = 1 ,31136   ,452,452,452
BEGIN DESCRIPTION:
Buck Creek 31135.96
END DESCRIPTION:
XS GIS Cut Line= 3
      1613760.66      6859834.44      1613951.62      6860348.75
      1614731.44      6860781.98
#Sta/Elev= 30
  4454.7 1739.86  4569.1 1738.79  4679.9 1734.82  4917.5 1728.64  4949.2 1726.64
  4959.8 1726.46  4967.6  1725.6  4981.2  1721.7  4991.8 1721.93    5001 1723.23
  5041.5 1724.88  5087.3 1724.16  5093.7 1723.62  5109.7 1724.29  5131.5 1724.24
  5190.2 1722.29  5212.7 1720.19  5213.5 1719.39    5214 1718.89    5235 1718.89
  5235.5 1719.39  5240.1 1721.53  5247.4 1723.29  5261.9 1725.27  5305.3 1726.17
  5321.4 1727.02  5359.1 1727.86  5527.3 1729.14  5689.7 1734.25  5895.4 1736.57
#Mann= 3 ,-1 , 0
  4454.7     .05       0  5213.5     .05       0  5235.5     .05       0
Bank Sta=5213.5,5235.5
XS Rating Curve= 0 ,0
Exp/Cntr=0.3,0.1

Type RM Length L Ch R = 1 ,30684   ,529,529,529
BEGIN DESCRIPTION:
Buck Creek 30684.19
END DESCRIPTION:
XS GIS Cut Line= 3
      1613342.61      6860580.84      1613856.49       6860723.2
       1614641.5      6860858.37
#Sta/Elev= 30
    4468 1733.19  4668.1 1729.66    4844 1727.55  4884.2  1726.7  4889.4 1726.87
  4916.7 1725.79  4923.7 1724.93  4928.9 1725.09  4937.4 1723.26  4947.8 1722.08
  4963.2 1721.75  4968.6 1720.74  4978.9 1719.96  4989.3 1721.59  5009.9 1721.12
    5020 1722.38  5040.3 1722.54  5050.5 1720.69  5051.1 1719.26  5051.6 1718.76
    5073 1718.76  5073.5 1719.26  5111.3 1719.44  5141.8 1720.81  5182.4 1723.88
  5192.5 1724.27  5456.3 1727.81  5591.4 1730.95  5646.2 1732.65  5797.8 1734.89
#Mann= 3 ,-1 , 0
    4468     .05       0  5051.1     .05       0  5073.5     .05       0
Bank Sta=5051.1,5073.5
XS Rating Curve= 0 ,0
Exp/Cntr=0.3,0.1

Type RM Length L Ch R = 1 ,30155   ,529,529,529
BEGIN DESCRIPTION:
Buck Creek 30155.41
END DESCRIPTION:
XS GIS Cut Line= 3
      1613236.66      6861082.15      1613800.88      6861203.67
      1614388.97      6861388.13
#Sta/Elev= 30
  4418.8 1731.72  4478.5 1728.23  4560.3 1725.08  4601.2 1722.54  4609.6 1721.84
  4621.7 1719.33  4652.4 1717.14  4672.8 1717.75    4724  1717.5  4806.9 1719.98
  4877.4 1720.63  4900.4 1720.36  4918.3 1718.35  4949.7 1717.98  4969.5  1718.7
  4979.7  1717.7  4984.7 1716.47  4985.2 1715.97  5006.7 1715.97  5007.2 1716.47
  5010.8 1718.38  5026.8 1719.79  5052.7 1720.37  5059.2 1721.55  5096.9 1721.01
  5129.3 1719.59    5147 1721.18  5178.4 1722.46  5426.4 1729.77  5612.3  1732.5
#Mann= 3 ,-1 , 0
  4418.8     .05       0  4984.7     .05       0  5007.2     .05       0
Bank Sta=4984.7,5007.2
XS Rating Curve= 0 ,0
Exp/Cntr=0.3,0.1

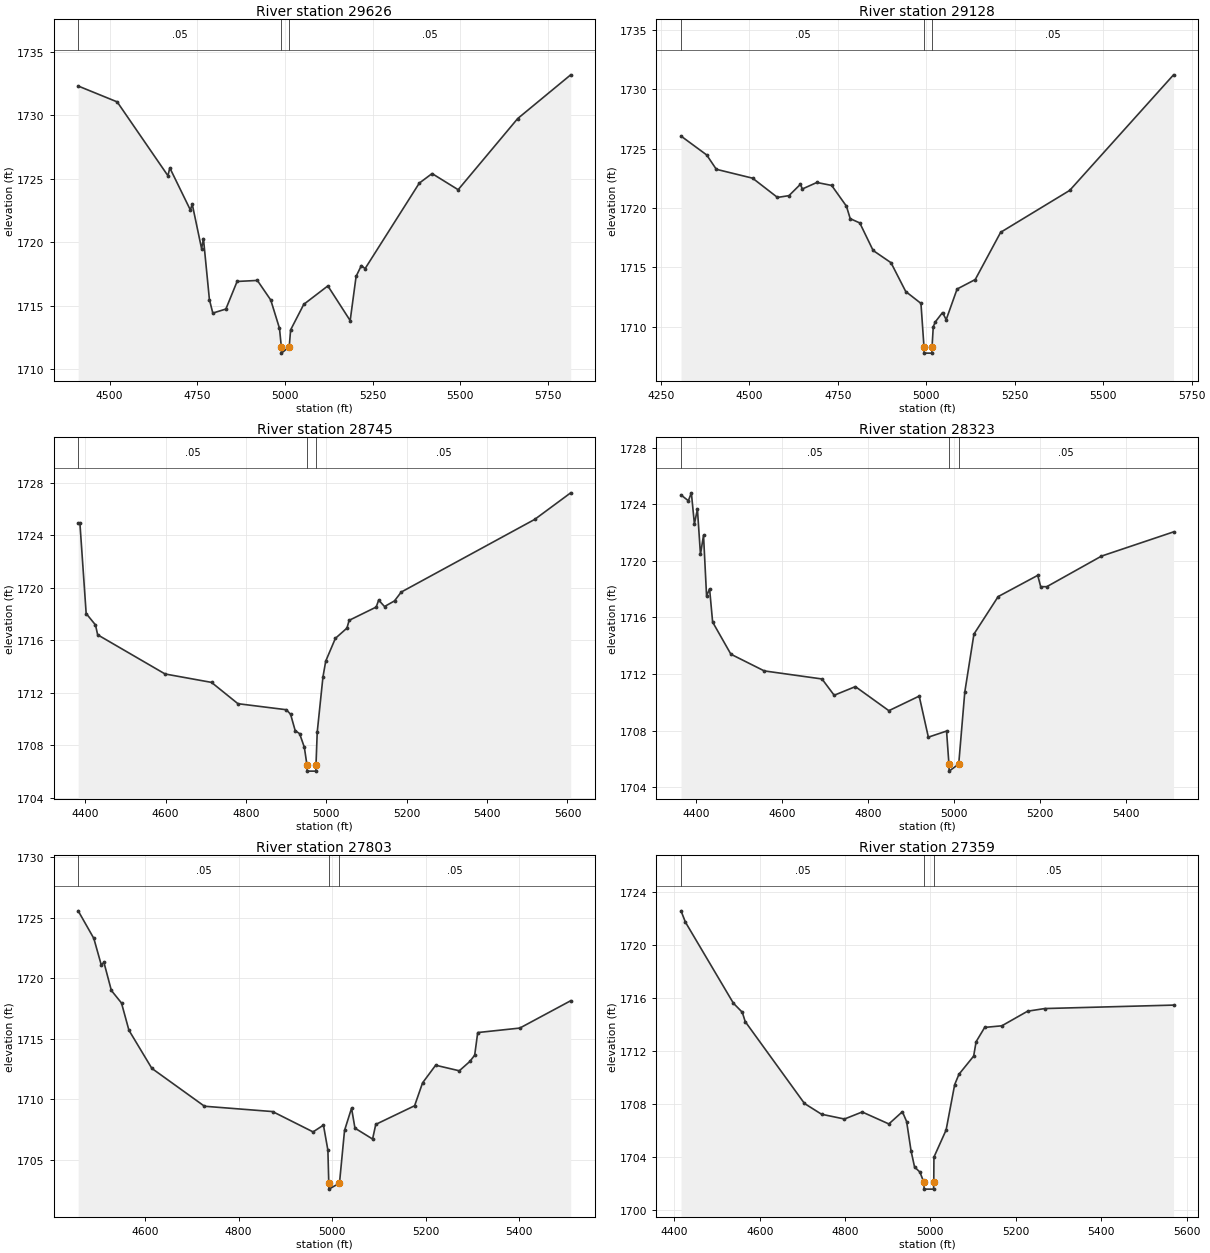
Type RM Length L Ch R = 1 ,29626   ,498,498,498
BEGIN DESCRIPTION:
Buck Creek 29626.11
END DESCRIPTION:
XS GIS Cut Line= 3
      1612989.27      6861453.24      1613551.31      6861635.53
      1614317.34      6861906.78
#Sta/Elev= 30
  4410.7  1732.3  4521.9 1731.05  4666.5 1725.24  4671.8 1725.86  4730.5 1722.54
  4735.7 1723.01  4762.4  1719.5  4767.7 1720.29  4784.7 1715.49  4794.4 1714.43
  4831.6 1714.75  4863.6 1716.92  4921.3    1717  4959.5 1715.46  4984.4 1713.23
  4989.6 1711.78  4990.1 1711.28  5012.1 1711.78  5016.1 1713.11  5053.6 1715.12
  5122.2 1716.57  5185.8 1713.84  5202.7 1717.32  5217.6 1718.17  5228.3 1717.93
  5382.8 1724.66  5419.2 1725.41  5493.5 1724.14  5663.2 1729.74  5814.2 1733.18
#Mann= 3 ,-1 , 0
  4410.7     .05       0  4989.6     .03       0  5012.1     .05       0
Bank Sta=4989.6,5012.1
XS Rating Curve= 0 ,0
Exp/Cntr=0.3,0.1

Type RM Length L Ch R = 1 ,29128   ,383,383,383
BEGIN DESCRIPTION:
Buck Creek 29127.65
END DESCRIPTION:
XS GIS Cut Line= 3
      1612748.61      6861882.04      1613408.37      6862088.22
      1614090.96       6862246.4
#Sta/Elev= 30
  4306.9 1726.05  4379.4 1724.46  4406.7 1723.25  4509.3  1722.5  4579.5 1720.88
    4612 1721.03  4644.5 1721.99  4649.7 1721.59  4690.8 1722.14  4732.7 1721.89
  4774.4 1720.14  4785.1 1719.09  4812.1 1718.73  4849.8 1716.41  4900.3 1715.38
    4942 1712.95    4985 1711.95  4993.6 1708.26  4994.1 1707.76  5015.8 1707.76
  5016.3 1708.26  5019.8 1709.99  5025.5 1710.39    5046 1711.18  5056.3 1710.58
  5087.1 1713.16  5138.4 1713.96  5210.2 1717.94  5405.3 1721.47  5698.8 1731.21
#Mann= 3 ,-1 , 0
  4306.9     .05       0  4993.6     .05       0  5016.3     .05       0
Bank Sta=4993.6,5016.3
XS Rating Curve= 0 ,0
Exp/Cntr=0.3,0.1

Type RM Length L Ch R = 1 ,28745   ,422,422,422
BEGIN DESCRIPTION:
Buck Creek 28744.57
END DESCRIPTION:
XS GIS Cut Line= 3
      1612742.25       6862184.7      1613308.69      6862438.62
      1613891.22      6862601.04
#Sta/Elev= 30
  4382.6 1724.93  4386.9 1724.93  4402.5 1718.04  4425.7 1717.17  4431.1 1716.42
  4598.9 1713.44  4714.4  1712.8  4780.1 1711.18  4900.7 1710.72  4911.2 1710.37
  4922.6 1709.13  4933.6  1708.9  4945.4 1707.86  4951.7 1706.55  4952.2 1706.05
  4973.9 1706.05  4974.4 1706.55  4977.4 1709.01  4991.7 1713.22  4998.6 1714.42
  5022.6 1716.15  5051.4 1716.93  5056.8 1717.52  5124.1 1718.53  5130.3 1719.06
  5144.9 1718.57  5169.7    1719  5186.4 1719.67  5518.6  1725.2  5608.1 1727.22
#Mann= 3 ,-1 , 0
  4382.6     .05       0  4951.7     .05       0  4974.4     .05       0
Bank Sta=4951.7,4974.4
XS Rating Curve= 0 ,0
Exp/Cntr=0.3,0.1

Type RM Length L Ch R = 1 ,28323   ,520,520,520
BEGIN DESCRIPTION:
Buck Creek 28323.31
END DESCRIPTION:
XS GIS Cut Line= 3
      1612555.63      6862243.28       1613002.7      6862696.87
       1613367.3      6863052.79
#Sta/Elev= 30
  4365.1 1724.65  4382.2 1724.24  4389.2  1724.8  4396.3  1722.6  4403.3 1723.65
  4410.4 1720.45  4417.5  1721.8  4424.6 1717.51  4431.6 1718.02  4438.7 1715.67
  4481.2  1713.4  4558.9 1712.22  4693.3 1711.65  4721.6  1710.5    4771 1711.11
  4848.9 1709.41  4919.5 1710.44  4940.8 1707.54  4983.2 1707.97  4988.7 1705.64
  4989.2 1705.14  5011.5 1705.64  5025.6 1710.72  5046.9 1714.82  5103.3 1717.47
  5195.4 1718.97  5202.3 1718.17  5216.5 1718.17  5343.8 1720.33  5511.5 1722.04
#Mann= 3 ,-1 , 0
  4365.1     .05       0  4988.7     .03       0  5011.5     .05       0
Bank Sta=4988.7,5011.5
XS Rating Curve= 0 ,0
Exp/Cntr=0.3,0.1

Type RM Length L Ch R = 1 ,27803   ,444,444,444
BEGIN DESCRIPTION:
Buck Creek 27802.9
END DESCRIPTION:
XS GIS Cut Line= 3
      1612244.88      6862321.42      1612511.82      6862792.79
      1612737.09      6863252.45
#Sta/Elev= 30
    4457 1725.59  4490.5 1723.31  4506.4 1721.12  4512.1 1721.33    4528 1719.01
  4549.7 1717.97  4565.6 1715.72  4614.6 1712.57  4727.2 1709.44  4872.9    1709
  4959.5 1707.32  4981.7 1707.88  4991.2 1705.81  4993.1 1703.09  4993.6 1702.59
    5016 1703.09  5026.8 1707.44  5041.8 1709.28  5049.1 1707.63  5086.8 1706.73
  5093.6 1707.94  5176.7 1709.48  5193.7 1711.37  5221.7 1712.83  5272.3 1712.37
  5294.8 1713.14  5305.2 1713.66  5311.7 1715.53  5401.7  1715.9  5510.6 1718.16
#Mann= 3 ,-1 , 0
    4457     .05       0  4993.1     .03       0    5016     .05       0
Bank Sta=4993.1,5016
XS Rating Curve= 0 ,0
Exp/Cntr=0.3,0.1

Type RM Length L Ch R = 1 ,27359   ,421,421,421
BEGIN DESCRIPTION:
Buck Creek 27358.96
END DESCRIPTION:
XS GIS Cut Line= 3
      1611998.05      6862429.96       1612160.8      6862996.35
      1612215.06      6863558.43
#Sta/Elev= 30
  4415.6 1722.56  4425.9 1721.71  4538.4  1715.6  4559.2 1714.92    4566 1714.22
  4704.9 1708.05  4744.9 1707.24  4798.5 1706.88  4840.1 1707.41  4902.6 1706.51
  4934.3 1707.43  4944.2 1706.69  4954.6 1704.48  4962.8 1703.27  4975.4 1702.88
  4984.7  1702.1  4985.2  1701.6  5007.3  1701.6  5007.8  1702.1  5008.2 1704.01
  5036.7 1706.05  5056.8 1709.47  5066.8 1710.25  5101.3 1711.62    5107  1712.7
  5127.1 1713.78  5167.3  1713.9  5227.6    1715  5267.8  1715.2  5569.6 1715.46
#Mann= 3 ,-1 , 0
  4415.6     .05       0  4984.7     .05       0  5007.8     .05       0
Bank Sta=4984.7,5007.8
XS Rating Curve= 0 ,0
Exp/Cntr=0.3,0.1

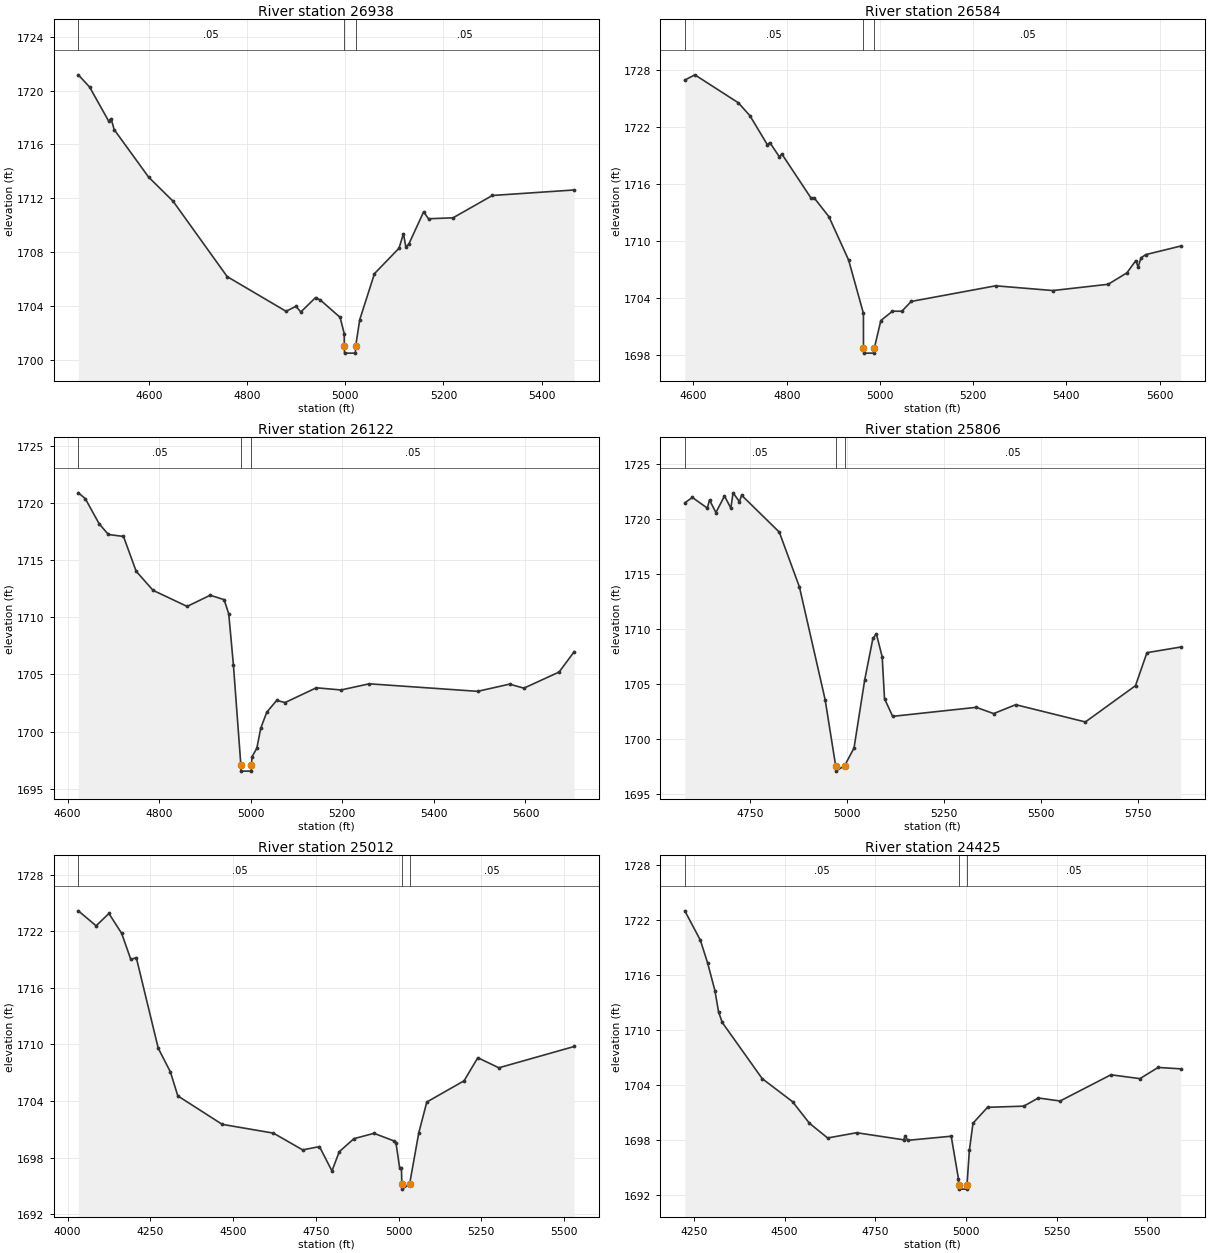
Type RM Length L Ch R = 1 ,26938   ,354,354,354
BEGIN DESCRIPTION:
Buck Creek 26937.51
END DESCRIPTION:
XS GIS Cut Line= 3
      1611772.35      6862495.03      1611752.82      6863039.75
      1611742.01      6863504.66
#Sta/Elev= 30
  4456.3 1721.17  4479.3 1720.26  4518.1 1717.73  4523.1 1717.91  4529.3  1717.1
  4599.4 1713.57  4649.4 1711.77  4759.5 1706.17  4879.5 1703.59  4899.6 1703.96
  4909.6 1703.54  4939.6 1704.61  4949.6 1704.42  4989.6 1703.14    4998 1701.93
  4998.1 1700.98  4998.6 1700.48  5020.7 1700.48  5021.2 1700.98  5029.6 1702.97
  5059.6 1706.39  5109.6 1708.28  5118.6 1709.36  5123.6 1708.36  5129.7  1708.6
  5159.7 1710.98  5169.7 1710.47  5219.7 1710.54  5299.7  1712.2  5466.4 1712.61
#Mann= 3 ,-1 , 0
  4456.3     .05       0  4998.1     .03       0  5021.2     .05       0
Bank Sta=4998.1,5021.2
XS Rating Curve= 0 ,0
Exp/Cntr=0.3,0.1

Type RM Length L Ch R = 1 ,26584   ,462,462,462
BEGIN DESCRIPTION:
Buck Creek 26583.67
END DESCRIPTION:
XS GIS Cut Line= 3
      1611638.31       6862446.1      1611499.43      6862845.37
      1611429.99      6863482.46
#Sta/Elev= 30
  4581.4 1726.98    4603 1727.53  4696.3 1724.58  4721.1 1723.22  4758.5 1720.16
  4763.8 1720.39  4784.3 1718.88  4789.6 1719.18  4851.8 1714.56  4858.7 1714.57
  4890.5 1712.57  4932.8    1708  4964.6 1702.37  4964.7 1698.68  4965.2 1698.18
  4987.3 1698.18  4987.8 1698.68    5002 1701.62  5026.9  1702.6    5047  1702.6
  5067.1 1703.63  5248.2 1705.28    5371 1704.78  5489.6 1705.44  5529.9 1706.65
  5548.8 1707.94  5553.8 1707.26    5560 1708.23  5570.1 1708.57    5645 1709.47
#Mann= 3 ,-1 , 0
  4581.4     .05       0  4964.7     .05       0  4987.8     .05       0
Bank Sta=4964.7,4987.8
XS Rating Curve= 0 ,0
Exp/Cntr=0.3,0.1

Type RM Length L Ch R = 1 ,26122   ,316,316,316
BEGIN DESCRIPTION:
Buck Creek 26122.02
END DESCRIPTION:
XS GIS Cut Line= 3
      1611035.89      6862413.07      1611091.45      6862788.07
      1611360.25      6863438.42
#Sta/Elev= 30
  4623.5 1720.91  4638.6 1720.41  4668.9  1718.2  4689.1 1717.26  4722.1 1717.09
  4749.8 1714.04  4786.6 1712.37  4861.1 1710.96  4911.5 1711.94  4941.9 1711.55
    4952  1710.3  4962.1 1705.87  4978.5 1697.03    4979 1696.53  5001.1 1696.53
  5001.6 1697.03  5002.6 1697.77  5013.3 1698.54  5021.9 1700.29    5035 1701.69
  5056.6 1702.72  5075.1 1702.54  5143.2 1703.83  5197.3 1703.64  5258.7 1704.18
  5495.5 1703.52  5565.2 1704.15  5596.6  1703.8  5673.4 1705.21  5706.3 1706.99
#Mann= 3 ,-1 , 0
  4623.5     .05       0  4978.5     .05       0  5001.6     .05       0
Bank Sta=4978.5,5001.6
XS Rating Curve= 0 ,0
Exp/Cntr=0.3,0.1

Type RM Length L Ch R = 1 ,25806   ,794,794,794
BEGIN DESCRIPTION:
Buck Creek 25805.75
END DESCRIPTION:
XS GIS Cut Line= 3
      1610612.97      6862521.92      1610808.29      6862896.93
      1611289.29      6863604.13
#Sta/Elev= 30
    4582 1721.48  4601.5 1721.97  4640.1    1721  4645.7 1721.74  4662.2  1720.6
  4684.3  1722.1  4700.7    1721  4706.4 1722.39  4722.8 1721.59  4728.5 1722.17
  4825.6 1718.82  4877.5 1713.83  4943.8 1703.58  4970.8 1697.59  4971.3 1697.09
    4994 1697.59  5018.2 1699.19  5045.9 1705.41  5066.9 1709.16  5075.8 1709.57
  5090.8 1707.48  5096.8 1703.68  5117.8 1702.07  5333.3 1702.89  5378.1 1702.32
    5435 1703.13  5614.6 1701.56  5743.8 1704.86  5773.3 1707.86  5860.1 1708.37
#Mann= 3 ,-1 , 0
    4582     .05       0  4970.8     .05       0    4994     .05       0
Bank Sta=4970.8,4994
XS Rating Curve= 0 ,0
Exp/Cntr=0.3,0.1

Type RM Length L Ch R = 1 ,25012   ,587,587,587
BEGIN DESCRIPTION:
Buck Creek 25011.82
END DESCRIPTION:
XS GIS Cut Line= 3
      1610347.34      6862691.18      1610795.27      6863553.18
      1610958.88      6864054.42
#Sta/Elev= 30
  4032.2 1724.17    4086 1722.58  4124.6 1723.89  4163.2 1721.78  4190.9 1719.01
  4207.4 1719.21  4273.7  1709.6  4310.4 1707.09  4332.9 1704.54  4467.1 1701.52
  4621.9 1700.59  4710.3 1698.81  4761.1 1699.16  4798.8 1696.58  4820.9 1698.62
  4865.1    1700  4925.8 1700.57  4986.5 1699.76  4992.2 1699.59  5003.5 1696.88
  5008.8 1696.88  5010.1 1695.15  5010.6 1694.65  5033.3 1695.15  5061.3 1700.63
  5085.5 1703.89  5198.1 1706.14  5239.7 1708.59  5303.2 1707.52  5530.9 1709.78
#Mann= 3 ,-1 , 0
  4032.2     .05       0  5010.1     .05       0  5033.3     .05       0
Bank Sta=5010.1,5033.3
XS Rating Curve= 0 ,0
Exp/Cntr=0.3,0.1

Type RM Length L Ch R = 1 ,24425   ,832,832,832
BEGIN DESCRIPTION:
Buck Creek 24424.77
END DESCRIPTION:
XS GIS Cut Line= 3
      1610368.94      6862815.05      1610319.02      6863591.97
      1610297.32      6864180.04
#Sta/Elev= 30
  4224.9 1723.04  4267.9 1719.83    4288 1717.33    4308 1714.33    4318 1712.02
  4328.1 1710.87  4438.3 1704.74  4521.9 1702.23  4568.6 1699.87  4618.7 1698.27
  4698.8 1698.84  4828.1 1698.07  4833.2 1698.51  4839.1 1698.01  4959.4 1698.46
  4979.4 1693.82  4979.7 1693.19  4980.2 1692.69  5002.5 1692.69    5003 1693.19
  5009.5 1696.93  5019.5 1699.88  5059.5 1701.61  5159.6 1701.74  5199.6 1702.63
  5259.6  1702.3  5399.7 1705.16  5479.8 1704.74  5529.8 1705.96  5591.9 1705.81
#Mann= 3 ,-1 , 0
  4224.9     .05       0  4979.7     .05       0    5003     .05       0
Bank Sta=4979.7,5003
XS Rating Curve= 0 ,0
Exp/Cntr=0.3,0.1

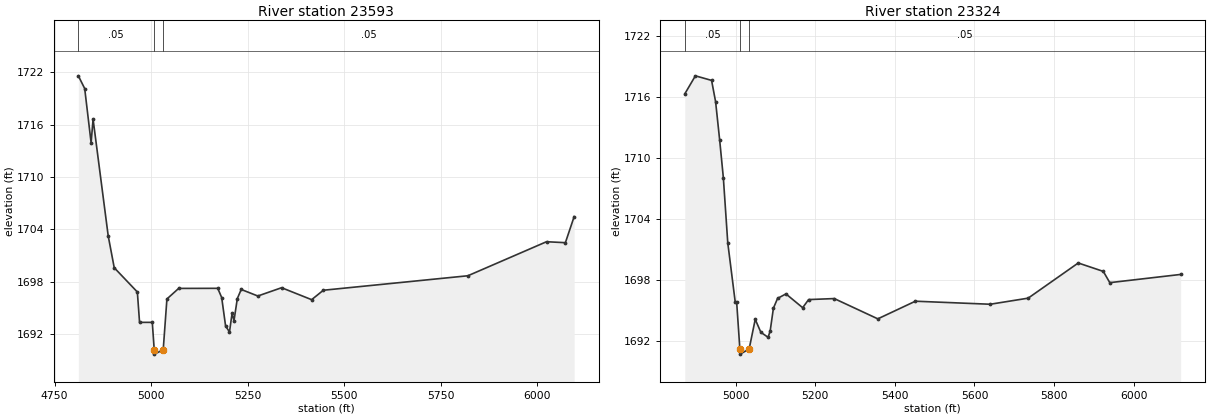
Type RM Length L Ch R = 1 ,23593   ,269,269,269
BEGIN DESCRIPTION:
Buck Creek 23592.64
END DESCRIPTION:
XS GIS Cut Line= 4
      1609874.14      6862951.74       1609906.7      6863140.58
      1609995.67      6863689.63      1610162.77      6864199.62
#Sta/Elev= 30
  4811.5 1721.58    4828 1720.12  4844.6 1713.91  4849.7 1716.61  4888.9 1703.24
  4904.5 1699.59  4964.4 1696.81  4970.1 1693.33  5003.1 1693.33  5008.1 1690.19
  5008.6 1689.69  5031.4 1690.19    5041 1696.01  5071.4 1697.22  5172.7 1697.23
  5182.9 1696.17    5193 1692.91  5203.1 1692.23  5209.8 1694.37  5214.8 1693.53
  5223.4 1696.06  5233.5  1697.1  5276.5 1696.35  5338.1  1697.3  5415.9 1695.93
  5446.2 1697.01  5820.7 1698.67  6024.4 1702.57  6073.3 1702.46    6096 1705.45
#Mann= 3 ,-1 , 0
  4811.5     .05       0  5008.1     .05       0  5031.4     .05       0
Bank Sta=5008.1,5031.4
XS Rating Curve= 0 ,0
Exp/Cntr=0.3,0.1

Type RM Length L Ch R = 1 ,23324   ,648,648,648
BEGIN DESCRIPTION:
Buck Creek 23324.16
END DESCRIPTION:
XS GIS Cut Line= 3
      1609661.46      6863131.87      1609685.34      6863259.94
      1610023.84      6864323.18
#Sta/Elev= 30
    4872 1716.33  4898.6 1718.11  4939.3 1717.66  4949.4 1715.56  4959.6 1711.79
  4968.9 1708.05    4980 1701.63  4998.7 1695.81  5002.3 1695.81  5010.4 1691.16
  5010.9 1690.66  5033.7 1691.16    5049 1694.09  5063.2 1692.81  5081.3 1692.32
  5086.5 1692.93  5094.7 1695.19  5105.2 1696.16  5126.2  1696.6  5168.2 1695.24
  5183.2 1696.04  5247.6 1696.14  5357.1 1694.14  5451.5 1695.88  5639.6 1695.58
  5734.9 1696.18  5860.8 1699.65  5923.8 1698.82  5940.1 1697.71  6118.1 1698.52
#Mann= 3 ,-1 , 0
    4872     .05       0  5010.4     .05       0  5033.7     .05       0
Bank Sta=5010.4,5033.7
XS Rating Curve= 0 ,0
Exp/Cntr=0.3,0.1