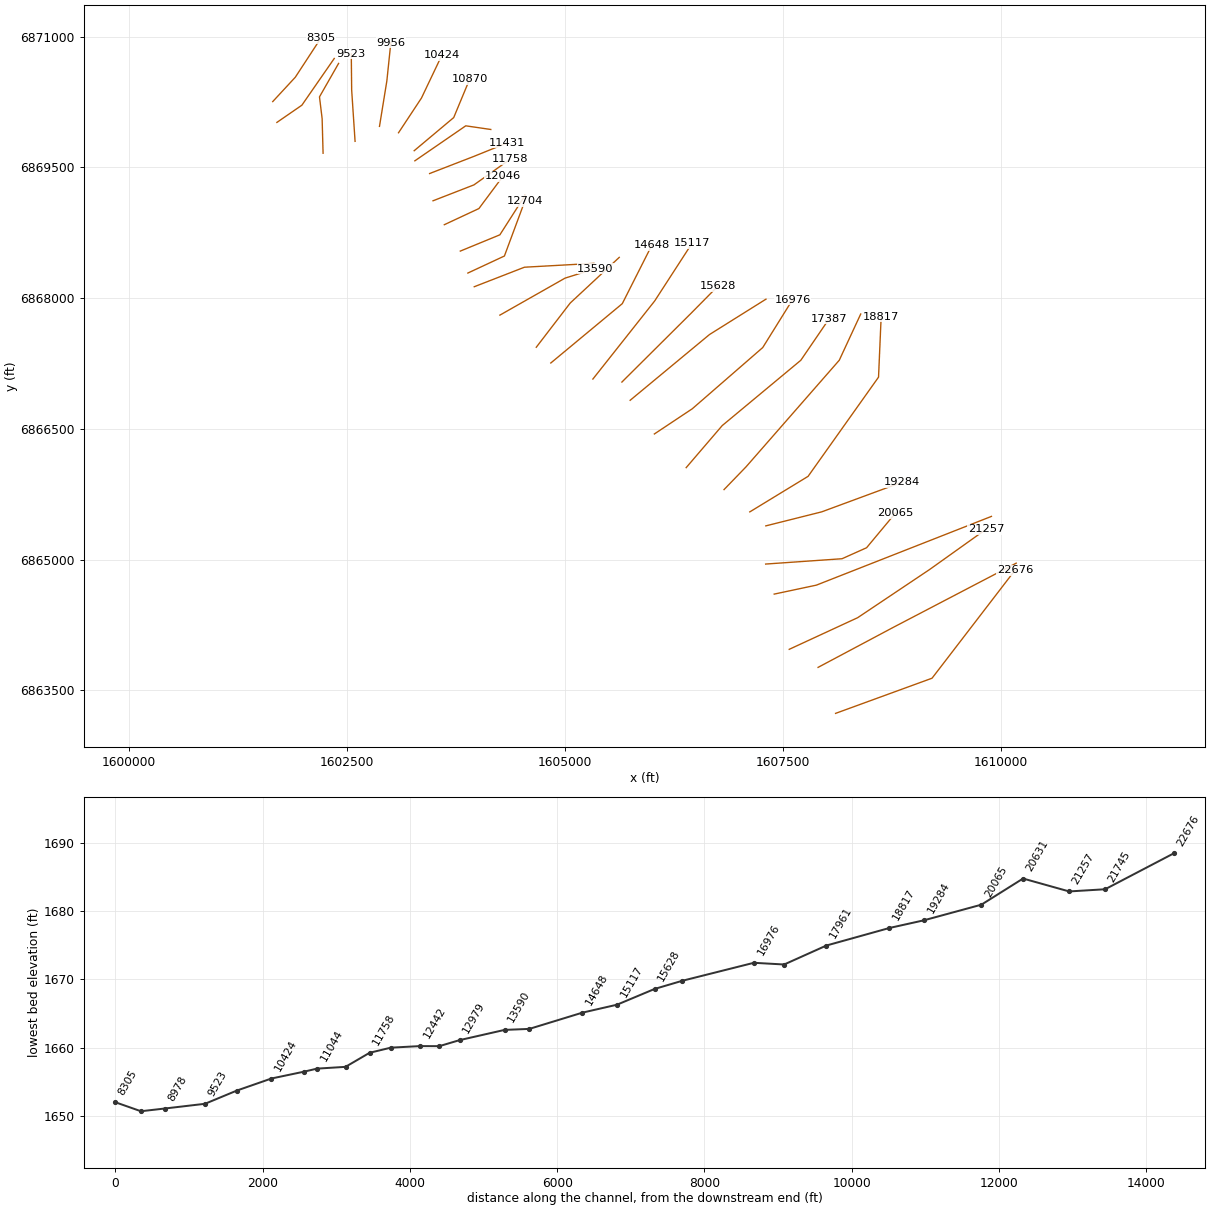
HEC-RAS study Buck Creek.prj: Buck Creek Base Level Engineering

--- Buck Creek.g01 (geometry) --- (continued)

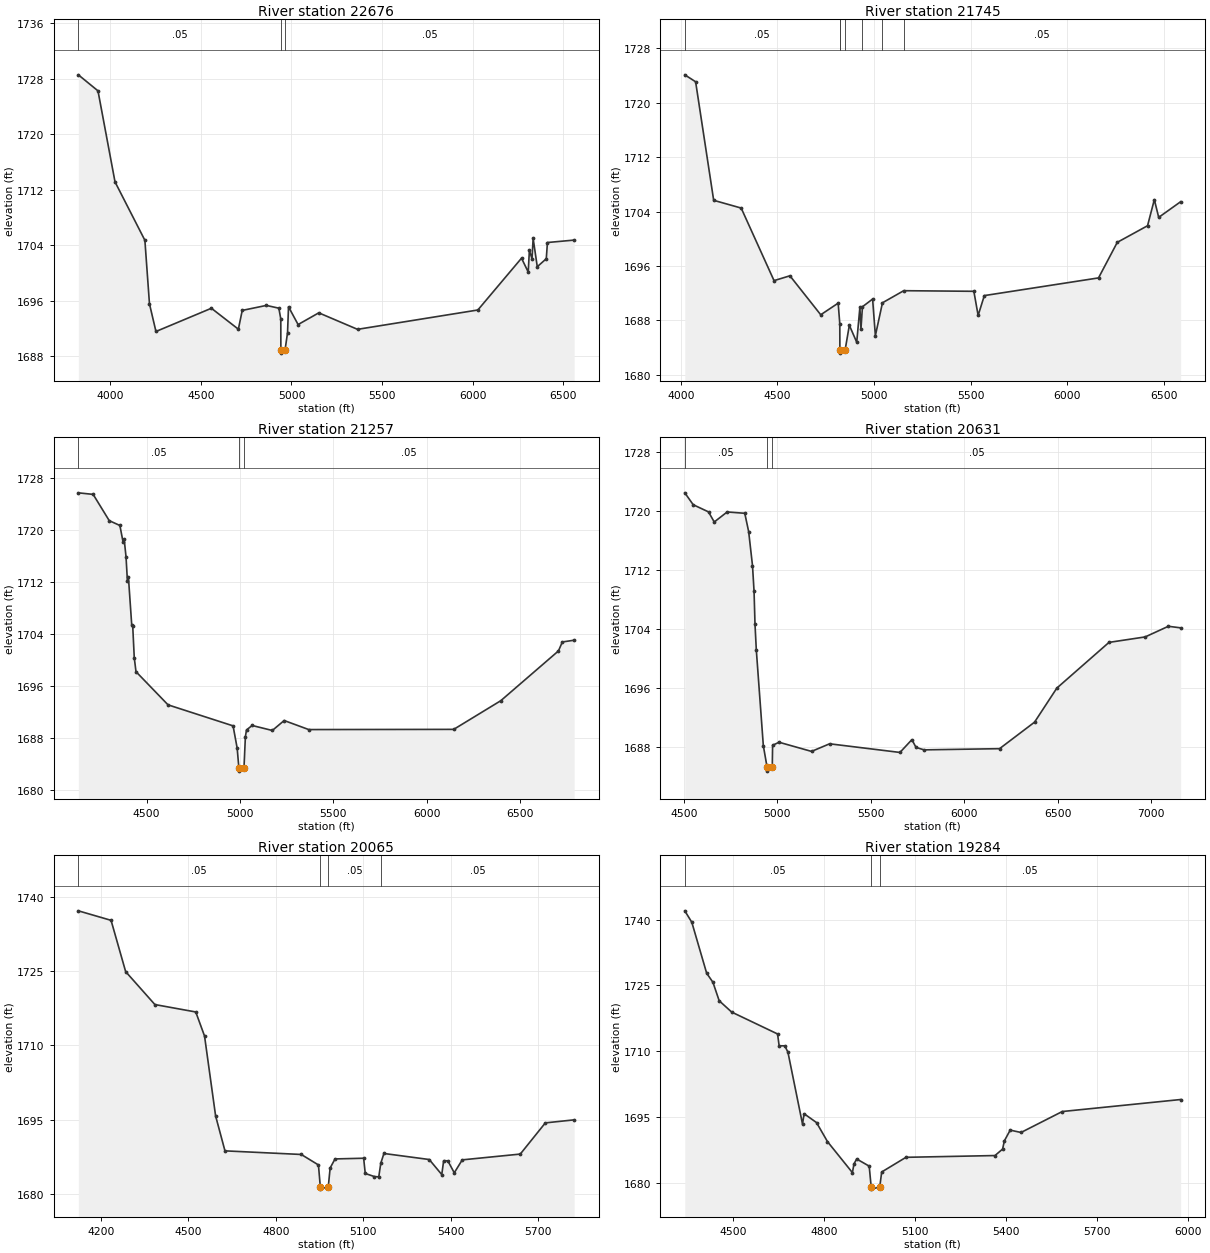
Type RM Length L Ch R = 1 ,22676   ,931,931,931
BEGIN DESCRIPTION:
Buck Creek 24659.955
END DESCRIPTION:
XS GIS Cut Line= 3
      1608104.71      6863237.06      1609210.54      6863640.44
      1610161.01      6864878.59
#Sta/Elev= 30
  3822.9 1728.58  3931.4 1726.27  4025.5 1713.14  4190.4 1704.72  4215.7 1695.56
  4251.5 1691.57  4557.7 1694.92  4706.7  1691.9    4728 1694.61  4861.3 1695.33
  4930.2 1694.93  4940.9 1693.37  4941.3 1688.95  4941.8 1688.45  4964.7 1688.95
  4978.2  1691.4  4983.5 1695.13  5036.5 1692.57  5150.7 1694.26  5364.6 1691.88
  6029.1 1694.67  6270.2 1702.14  6307.3 1700.14  6313.6 1703.25  6328.1 1702.07
  6334.4 1704.99  6357.2 1700.91    6407 1702.06  6413.3  1704.4  6560.9 1704.75
#Mann= 3 ,-1 , 0
  3822.9     .05       0  4941.3     .05       0  4964.7     .05       0
Bank Sta=4941.3,4964.7
XS Rating Curve= 0 ,0
Exp/Cntr=0.3,0.1

Type RM Length L Ch R = 1 ,21745   ,488,488,488
BEGIN DESCRIPTION:
Buck Creek 21745.408
END DESCRIPTION:
XS GIS Cut Line= 3
      1607904.15      6863764.82      1608768.57      6864225.04
      1610175.62      6864960.36
#Sta/Elev= 30
  4020.7 1724.12  4076.7  1723.1  4170.2 1705.67  4312.6 1704.53  4482.7 1693.86
  4564.9 1694.57  4724.4 1688.84  4814.7 1690.55  4823.1 1687.51  4823.6  1683.7
  4824.1  1683.2    4851  1683.7  4872.5  1687.3  4910.8  1684.8  4927.1 1689.92
  4932.7 1686.76  4940.4 1690.02    4993 1691.15  5007.3 1685.77    5044  1690.6
  5154.1 1692.38  5517.2 1692.29  5539.3 1688.74  5571.4 1691.66  6162.6 1694.26
  6259.7 1699.49  6416.3 1701.93  6451.5 1705.77  6474.1 1703.16  6587.6 1705.46
#Mann= 7 ,-1 , 0
  4020.7     .05       0  4823.1     .12       0  4823.6     .03       0
    4851     .12       0  4940.4     .05       0    5044     .12       0
  5154.1     .05       0
Bank Sta=4823.6,4851
XS Rating Curve= 0 ,0
Exp/Cntr=0.3,0.1

Type RM Length L Ch R = 1 ,21257   ,626,626,626
BEGIN DESCRIPTION:
Buck Creek 21158.629
END DESCRIPTION:
XS GIS Cut Line= 4
      1607573.38      6863971.83      1608358.51      6864335.09
      1609181.06      6864886.35      1609831.05      6865350.01
#Sta/Elev= 30
  4134.9 1725.67  4214.2 1725.43  4300.4 1721.39  4357.3 1720.65  4374.7 1718.05
  4380.2 1718.55  4390.1 1715.85  4397.6 1712.11  4403.1 1712.67  4420.6 1705.38
  4426.1 1705.13  4434.2 1700.33  4443.5 1698.17    4615 1693.07  4963.1 1689.84
  4985.1  1686.4  4994.1 1683.38  4994.6 1682.88  5021.5 1683.38    5029 1688.18
    5035 1689.21    5065  1689.9  5173.1 1689.13  5236.5 1690.66  5368.2 1689.27
    6144  1689.3    6396 1693.71  6704.5 1701.36  6725.4 1702.74  6788.6 1703.01
#Mann= 3 ,-1 , 0
  4134.9     .05       0  4994.1     .05       0  5021.5     .05       0
Bank Sta=4994.1,5021.5
XS Rating Curve= 0 ,0
Exp/Cntr=0.3,0.1

Type RM Length L Ch R = 1 ,20631   ,566,566,566
BEGIN DESCRIPTION:
Buck Creek 20630.838
END DESCRIPTION:
XS GIS Cut Line= 3
      1607401.04      6864605.38      1607884.44      6864708.12
      1609891.45      6865496.78
#Sta/Elev= 30
  4505.8 1722.45  4550.7 1720.84  4632.5 1719.87  4663.2  1718.5  4732.3 1719.86
  4826.4 1719.68  4847.2  1717.2  4867.7  1712.6    4876 1709.14  4881.1 1704.65
  4888.1 1701.18  4925.6 1688.22  4945.9 1685.27  4946.4 1684.77  4973.4 1685.27
  4975.2 1688.27  5009.7 1688.68  5183.3 1687.44    5280 1688.47    5656  1687.3
  5719.7 1689.03    5742 1687.98  5784.9 1687.65  6188.5 1687.81  6375.5  1691.4
  6494.6 1696.01  6773.4  1702.2  6966.8 1702.94  7090.9 1704.38  7156.4 1704.17
#Mann= 3 ,-1 , 0
  4505.8     .05       0  4945.9     .05       0  4973.4     .05       0
Bank Sta=4945.9,4973.4
XS Rating Curve= 0 ,0
Exp/Cntr=0.3,0.1

Type RM Length L Ch R = 1 ,20065   ,781,781,781
BEGIN DESCRIPTION:
Buck Creek 20064.892
END DESCRIPTION:
XS GIS Cut Line= 4
      1607302.98        6864950.      1608178.85      6865011.13
      1608460.01       6865137.2      1608789.85      6865533.19
#Sta/Elev= 30
    4122 1737.15  4234.3 1735.23  4284.4 1724.87  4384.7 1718.22    4525 1716.72
  4555.1 1711.86  4593.1 1695.72  4625.2 1688.67  4887.1 1687.94    4946 1685.82
  4952.3 1681.44  4952.8 1680.94  4979.8 1681.44  4986.1 1685.21  5002.9 1687.04
  5101.1 1687.18  5106.6  1684.1  5138.3 1683.47    5153 1683.43    5160 1686.18
  5170.7 1688.14  5326.2 1686.92  5369.2 1683.88  5375.7 1686.68    5390 1686.65
  5412.1 1684.24  5439.5 1686.85  5638.6 1688.02  5724.6 1694.32  5823.5 1694.93
#Mann= 4 ,-1 , 0
    4122     .05       0  4952.3     .07       0  4979.8     .05       0
    5160     .05       0
Bank Sta=4952.3,4979.8
XS Rating Curve= 0 ,0
Exp/Cntr=0.3,0.1

Type RM Length L Ch R = 1 ,19284   ,467,467,467
BEGIN DESCRIPTION:
Buck Creek 19509.893
END DESCRIPTION:
XS GIS Cut Line= 3
      1607305.03      6865388.01      1607945.54      6865548.84
      1608860.34      6865886.71
#Sta/Elev= 30
  4339.6 1741.98  4362.7 1739.38  4411.7 1727.79  4432.4 1725.72    4453 1721.52
  4494.2 1718.94  4645.6 1713.96  4650.8 1711.27  4669.5 1711.26  4679.8 1709.81
  4727.9 1693.45  4733.1 1695.81  4774.2 1693.79  4810.2 1689.47  4892.5 1682.41
  4897.7 1684.39  4906.6 1685.51  4947.9 1683.88  4954.4 1679.15  4954.9 1678.65
  4982.7 1679.15  4989.1 1682.55  5069.2 1685.89  5362.8 1686.29  5387.9 1687.76
  5393.8 1689.64    5413 1692.08  5448.7 1691.54  5584.8 1696.31  5975.2 1699.04
#Mann= 3 ,-1 , 0
  4339.6     .05       0  4954.4     .05       0  4982.7     .05       0
Bank Sta=4954.4,4982.7
XS Rating Curve= 0 ,0
Exp/Cntr=0.3,0.1

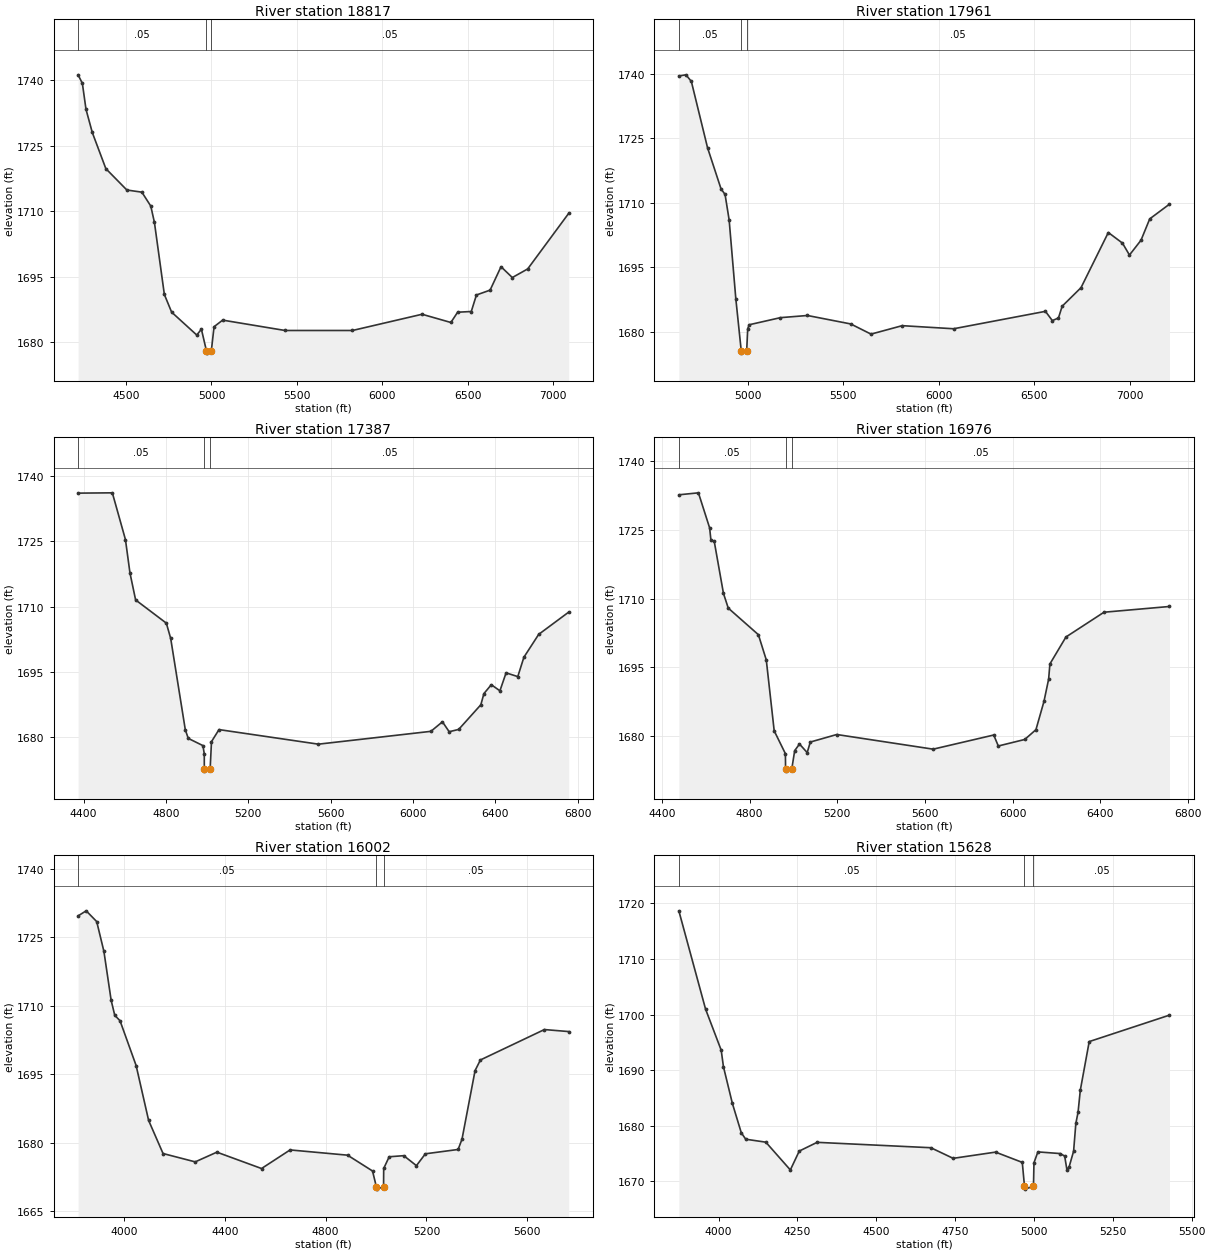
Type RM Length L Ch R = 1 ,18817   ,856,856,856
BEGIN DESCRIPTION:
Buck Creek 18816.73
END DESCRIPTION:
XS GIS Cut Line= 4
      1607121.16      6865548.32      1607789.54       6865956.3
      1608597.14      6867094.17      1608627.21      6867787.93
#Sta/Elev= 30
    4219 1741.19  4244.1 1739.25  4265.4  1733.3  4302.2    1728  4381.6 1719.73
  4504.7 1714.84  4592.6 1714.35  4644.8 1711.16  4666.1 1707.42  4724.2 1690.95
  4766.8  1686.9  4913.9 1681.67  4941.1    1683  4970.8 1678.03  4971.3 1677.53
  4999.2 1678.03  5015.2 1683.57  5065.5 1685.08    5431 1682.71  5825.7 1682.71
  6233.1 1686.42  6401.8 1684.54  6441.3 1686.89  6521.3 1687.05  6551.4 1690.83
  6631.4 1691.94  6695.4  1697.3  6761.6 1694.82  6851.6 1696.79  7091.8 1709.51
#Mann= 3 ,-1 , 0
    4219     .05       0  4970.8     .05       0  4999.2     .05       0
Bank Sta=4970.8,4999.2
XS Rating Curve= 0 ,0
Exp/Cntr=0.3,0.1

Type RM Length L Ch R = 1 ,17961   ,574,574,574
BEGIN DESCRIPTION:
Buck Creek 17961.4
END DESCRIPTION:
XS GIS Cut Line= 4
      1606825.98      6865804.37      1607077.73       6866064.8
      1608146.84      6867287.91      1608392.85      6867818.31
#Sta/Elev= 30
  4637.7 1739.55  4674.9 1739.82  4703.2 1738.29  4788.1 1722.83  4858.8 1713.24
  4879.9 1711.95  4901.3 1706.01  4936.5 1687.54  4964.8 1675.46  4965.3 1674.96
  4993.2 1675.46  4998.7 1680.68  5007.1 1681.58  5170.4 1683.23  5311.8 1683.73
  5538.6 1681.76  5644.9 1679.39  5808.2 1681.36  6077.8 1680.64    6559  1684.7
  6595.1 1682.54  6627.2 1683.15  6646.6 1685.89  6745.5 1690.22  6888.5 1703.07
  6962.7  1700.6  6999.3 1697.82  7059.8 1701.27  7105.6 1706.25  7209.1 1709.68
#Mann= 3 ,-1 , 0
  4637.7     .05       0  4964.8     .03       0  4993.2     .05       0
Bank Sta=4964.8,4993.2
XS Rating Curve= 0 ,0
Exp/Cntr=0.3,0.1

Type RM Length L Ch R = 1 ,17387   ,411,411,411
BEGIN DESCRIPTION:
Buck Creek 17387.21
END DESCRIPTION:
XS GIS Cut Line= 4
      1606391.99      6866056.15       1606804.3      6866537.89
      1607706.18      6867287.83      1608031.49      6867764.58
#Sta/Elev= 30
  4372.9 1736.11  4539.4 1736.18  4603.1 1725.43  4625.1 1717.74  4652.5 1711.55
  4801.8 1706.21  4822.9 1702.71    4894 1681.69  4908.3 1679.71  4979.6 1678.05
  4986.2 1676.16  4986.3 1672.68  4986.8 1672.18  5014.7 1672.68  5021.2 1678.96
  5057.7 1681.73  5540.7 1678.38  6087.4 1681.33  6143.5 1683.52  6176.2 1681.24
  6222.4 1681.77  6330.1 1687.44    6345 1690.01  6380.9 1692.05  6422.8 1690.65
  6452.7 1694.78  6509.6 1693.92  6539.4 1698.38  6611.2 1703.63  6757.1 1708.75
#Mann= 3 ,-1 , 0
  4372.9     .05       0  4986.3     .05       0  5014.7     .05       0
Bank Sta=4986.3,5014.7
XS Rating Curve= 0 ,0
Exp/Cntr=0.3,0.1

Type RM Length L Ch R = 1 ,16976   ,974,974,974
BEGIN DESCRIPTION:
Buck Creek 16916.97
END DESCRIPTION:
XS GIS Cut Line= 4
      1606027.39      6866442.41      1606462.47      6866731.92
      1607269.57      6867433.73      1607610.75      6867981.87
#Sta/Elev= 30
  4477.4 1732.58  4566.7 1733.01  4617.8 1725.38  4623.8 1722.69  4638.8 1722.45
  4680.9 1711.12  4702.7 1707.92  4840.2 1702.13  4876.2 1696.64  4912.3  1681.2
  4963.4 1676.23  4964.2 1672.93  4964.7 1672.43  4992.6 1672.93  5005.8 1676.89
  5027.7 1678.33  5062.8 1676.46    5077 1678.76  5197.6  1680.4  5637.3 1677.21
  5913.6 1680.29  5934.4  1677.9    6055 1679.32  6106.1 1681.45  6142.7  1687.6
    6164 1692.46  6169.8 1695.76    6243 1701.63  6416.5 1707.02  6715.2 1708.27
#Mann= 3 ,-1 , 0
  4477.4     .05       0  4964.2     .05       0  4992.6     .05       0
Bank Sta=4964.2,4992.6
XS Rating Curve= 0 ,0
Exp/Cntr=0.3,0.1

Type RM Length L Ch R = 1 ,16002   ,374,374,374
BEGIN DESCRIPTION:
Buck Creek 16002.48
END DESCRIPTION:
XS GIS Cut Line= 3
      1605749.64      6866828.72      1606659.14      6867583.04
      1607306.73      6867988.98
#Sta/Elev= 30
  3818.4 1729.74  3850.6 1730.85  3892.3 1728.49  3920.9 1721.94  3949.6 1711.21
  3963.9 1707.93  3984.8 1706.73  4048.6 1696.91  4098.2 1684.86  4155.4  1677.6
    4283 1675.77  4368.9  1677.9    4546 1674.31  4659.3 1678.39  4887.2 1677.24
  4986.2 1673.77  5001.5 1670.29    5002 1669.79    5030 1670.29  5030.5 1674.32
  5052.3 1676.89  5110.1 1677.13  5160.3 1674.94  5195.8 1677.54  5325.7 1678.49
  5341.1 1680.76  5392.9  1695.8  5414.1 1698.13  5667.8  1704.8  5764.3 1704.36
#Mann= 3 ,-1 , 0
  3818.4     .05       0  5001.5     .05       0    5030     .05       0
Bank Sta=5001.5,5030
XS Rating Curve= 0 ,0
Exp/Cntr=0.3,0.1

Type RM Length L Ch R = 1 ,15628   ,511,511,511
BEGIN DESCRIPTION:
Buck Creek 15627.944
END DESCRIPTION:
XS GIS Cut Line= 3
      1605655.01      6867038.01      1606453.09       6867832.2
      1606754.98      6868137.98
#Sta/Elev= 30
  3874.1 1718.68  3958.9 1700.98  4008.4  1693.6  4015.5 1690.63  4043.8 1684.03
  4072.1 1678.74  4086.2 1677.58  4149.9 1677.05  4227.6 1672.05  4255.9 1675.45
  4312.5 1677.02  4673.1 1676.05  4743.8 1674.14  4878.2 1675.26    4963 1673.41
    4970  1669.1  4970.5  1668.6  4998.5  1669.1    5000 1673.34  5012.5  1675.3
  5083.2    1675  5097.4 1674.55  5104.5 1672.08  5111.5 1672.61  5125.7 1675.43
  5132.8 1680.42  5139.8 1682.42  5146.9 1686.38  5175.2 1695.15  5429.7 1699.91
#Mann= 3 ,-1 , 0
  3874.1     .05       0    4970     .05       0  4998.5     .05       0
Bank Sta=4970,4998.5
XS Rating Curve= 0 ,0
Exp/Cntr=0.3,0.1

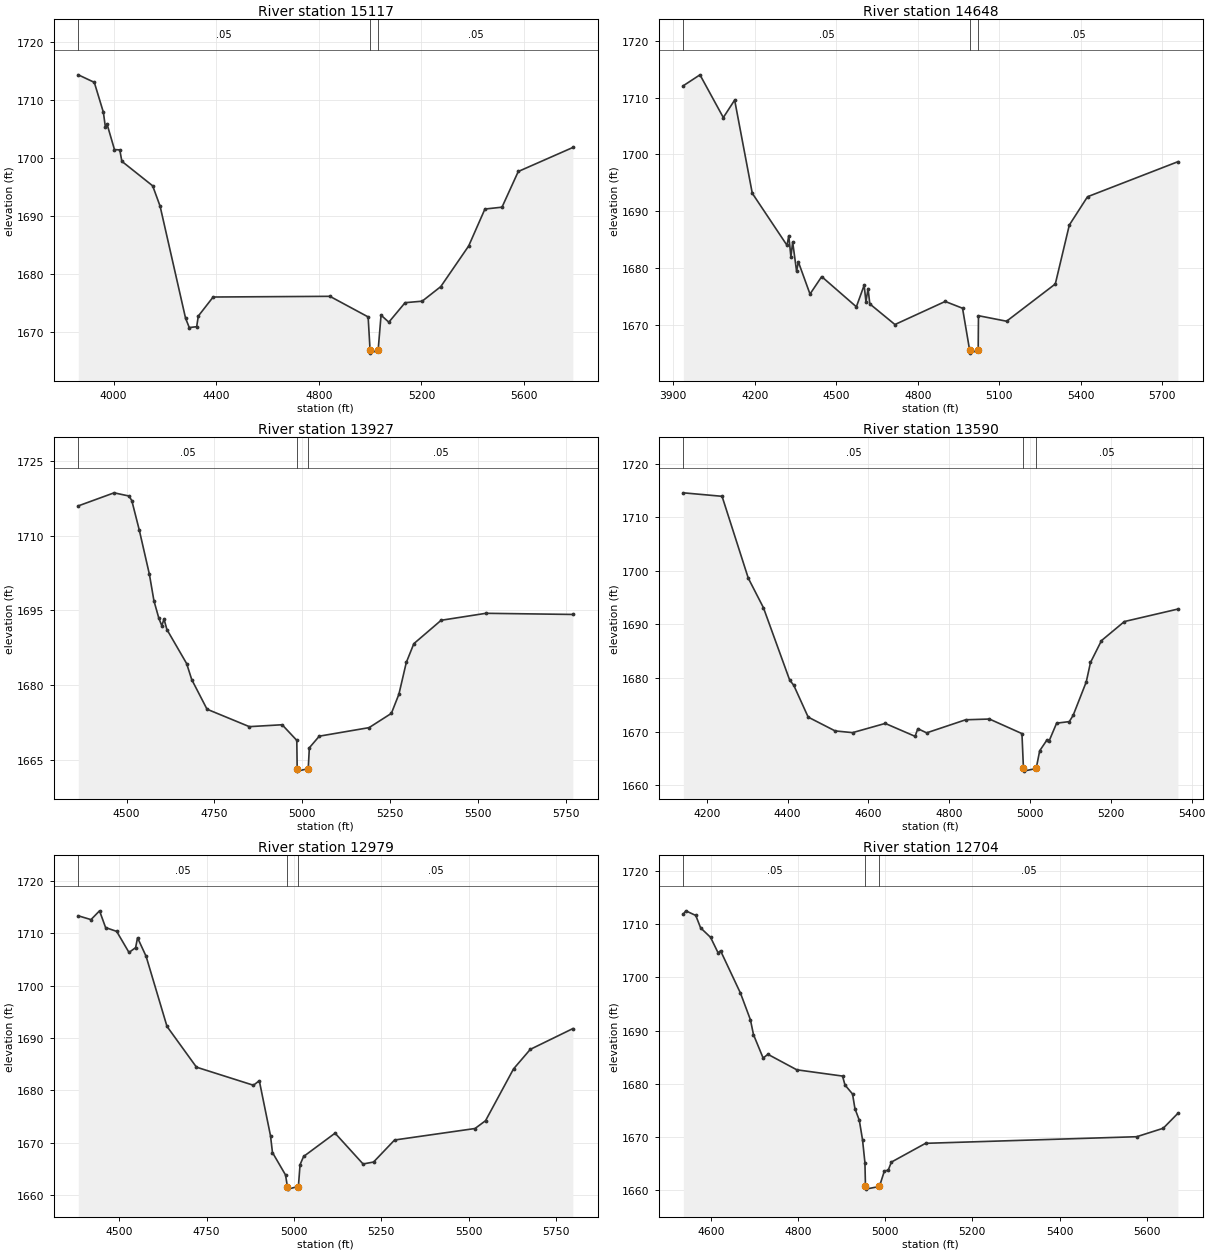
Type RM Length L Ch R = 1 ,15117   ,469,469,469
BEGIN DESCRIPTION:
Buck Creek 15117.14
END DESCRIPTION:
XS GIS Cut Line= 3
      1605322.44      6867072.43       1606030.8      6867968.29
       1606457.9      6868628.04
#Sta/Elev= 30
  3862.3  1714.4  3924.8  1713.1  3960.1 1707.94  3968.1 1705.34  3974.5 1705.88
  4003.4 1701.48  4024.2 1701.42  4032.2 1699.45  4152.4 1695.21  4181.3 1691.69
  4280.6 1672.32  4295.1 1670.71  4323.9 1670.86  4330.3  1672.7  4388.1 1675.99
  4843.3 1676.11  4992.3 1672.55  4999.9 1666.79  5000.4 1666.29  5031.3 1666.79
  5042.7 1672.85    5073 1671.64  5136.4 1675.01    5203 1675.27  5275.5 1677.79
  5384.3 1684.82  5447.6  1691.2  5514.2 1691.52  5577.6 1697.69  5790.3 1701.84
#Mann= 3 ,-1 , 0
  3862.3     .05       0  4999.9     .03       0  5031.3     .05       0
Bank Sta=4999.9,5031.3
XS Rating Curve= 0 ,0
Exp/Cntr=0.3,0.1

Type RM Length L Ch R = 1 ,14648   ,721,721,721
BEGIN DESCRIPTION:
Buck Creek 14647.77
END DESCRIPTION:
XS GIS Cut Line= 3
      1604839.83      6867256.49      1605659.27      6867937.04
      1605999.56      6868610.68
#Sta/Elev= 30
  3937.4 1712.07  3998.6 1713.98  4084.5 1706.48  4126.2 1709.55  4191.1 1693.19
  4318.9 1684.05  4325.4 1685.74  4333.2 1682.04  4339.7 1684.63  4354.1 1679.51
  4360.6 1681.15  4403.5  1675.5  4446.5 1678.56  4574.1 1673.26  4602.8 1677.05
  4609.3 1674.16  4617.1 1676.46  4623.6 1673.77    4716 1670.15    4901  1674.2
  4964.8 1673.01    4991 1665.63  4991.5 1665.13  5022.4 1665.63  5023.4  1671.7
  5126.9 1670.73  5306.2 1677.27  5357.8 1687.62  5424.7 1692.58  5757.3 1698.73
#Mann= 3 ,-1 , 0
  3937.4     .05       0    4991     .05       0  5022.4     .05       0
Bank Sta=4991,5022.4
XS Rating Curve= 0 ,0
Exp/Cntr=0.3,0.1

Type RM Length L Ch R = 1 ,13927   ,337,337,337
BEGIN DESCRIPTION:
Buck Creek 13926.73
END DESCRIPTION:
XS GIS Cut Line= 3
      1604673.17      6867437.06      1605062.05      6867943.99
      1605624.57      6868468.31
#Sta/Elev= 30
  4362.3 1715.94  4464.3 1718.56  4506.7 1717.92  4514.7    1717  4535.7 1711.18
  4564.8 1702.22  4577.7 1696.91  4591.9 1693.36  4600.1 1691.91  4606.4 1693.25
  4614.6 1691.15  4670.8 1684.32  4685.3 1681.11  4728.8 1675.17  4849.3 1671.67
  4942.7 1672.05  4984.4 1668.92  4985.5 1663.25    4986 1662.75    5017 1663.25
  5020.1 1667.43  5048.4 1669.76  5190.1 1671.47  5253.6 1674.33  5275.1 1678.18
  5296.1 1684.54  5317.6 1688.31  5395.3    1693  5522.8  1694.4  5770.2 1694.17
#Mann= 3 ,-1 , 0
  4362.3     .05       0  4985.5     .05       0    5017     .05       0
Bank Sta=4985.5,5017
XS Rating Curve= 0 ,0
Exp/Cntr=0.3,0.1

Type RM Length L Ch R = 1 ,13590   ,611,611,611
BEGIN DESCRIPTION:
Buck Creek 13590.41
END DESCRIPTION:
XS GIS Cut Line= 3
      1604256.37      6867805.84      1605003.77      6868230.33
      1605351.36      6868339.27
#Sta/Elev= 30
  4142.2 1714.58    4238 1713.93  4302.9 1698.64  4340.4 1693.12  4405.3 1679.61
  4415.4 1678.64  4451.1 1672.69  4517.8 1670.11    4561 1669.79  4641.8 1671.51
  4715.6  1669.1  4722.5 1670.53  4744.2 1669.75  4840.8 1672.19  4899.6 1672.33
  4980.1 1669.61  4983.8  1663.1  4984.3  1662.6  5015.3  1663.1    5024  1666.4
  5041.9 1668.41  5047.1  1668.2  5065.9 1671.56  5097.3 1671.85  5106.8 1673.02
  5139.2 1679.26  5149.7 1682.89  5176.9 1686.98  5233.6 1690.54    5366 1692.87
#Mann= 3 ,-1 , 0
  4142.2     .05       0  4983.8     .05       0  5015.3     .05       0
Bank Sta=4983.8,5015.3
XS Rating Curve= 0 ,0
Exp/Cntr=0.3,0.1

Type RM Length L Ch R = 1 ,12979   ,275,275,275
BEGIN DESCRIPTION:
Buck Creek 13315.053
END DESCRIPTION:
XS GIS Cut Line= 3
      1603962.11      6868131.37      1604537.58      6868355.27
      1605334.55       6868399.6
#Sta/Elev= 30
  4382.5 1713.36  4418.9 1712.63  4443.4 1714.31  4460.7 1711.11  4492.4 1710.38
  4527.7 1706.35  4546.6 1707.27  4552.2 1709.16  4576.7 1705.61  4636.5 1692.21
  4720.8 1684.42    4884 1680.96  4900.7 1681.83  4932.8  1671.3  4938.4  1668.1
  4975.8 1663.81  4981.1  1661.6  4981.6  1661.1  5012.6  1661.6  5017.4 1665.78
  5027.5 1667.34  5117.6  1671.8  5197.7 1665.91  5227.8 1666.28  5287.9 1670.49
  5518.2 1672.69  5548.3 1674.18  5628.4 1684.08  5676.4 1687.82  5798.2 1691.79
#Mann= 3 ,-1 , 0
  4382.5     .05       0  4981.1     .05       0  5012.6     .05       0
Bank Sta=4981.1,5012.6
XS Rating Curve= 0 ,0
Exp/Cntr=0.3,0.1

Type RM Length L Ch R = 1 ,12704   ,262,262,262
BEGIN DESCRIPTION:
Buck Creek 12703.51
END DESCRIPTION:
XS GIS Cut Line= 3
      1603889.19      6868288.56      1604307.98      6868483.85
      1604541.91      6869114.15
#Sta/Elev= 30
  4537.1 1711.91  4542.8 1712.53  4565.6 1711.66  4576.7 1709.33  4599.6 1707.54
  4616.9 1704.62  4622.4 1705.03  4668.2 1697.05    4691 1692.04    4698 1689.26
  4720.1 1684.86  4731.1 1685.56  4797.3 1682.65  4902.3 1681.47  4907.8  1679.8
  4925.2  1678.1  4930.7 1675.35  4940.7 1673.17  4948.1  1669.5  4953.6 1665.21
  4954.9 1660.72  4955.4 1660.22  4986.9 1660.72  4998.2 1663.62    5007 1663.78
  5014.3  1665.3  5092.7 1668.83    5577 1670.07  5637.8 1671.66  5671.5 1674.47
#Mann= 3 ,-1 , 0
  4537.1     .05       0  4954.9     .05       0  4986.9     .05       0
Bank Sta=4954.9,4986.9
XS Rating Curve= 0 ,0
Exp/Cntr=0.3,0.1

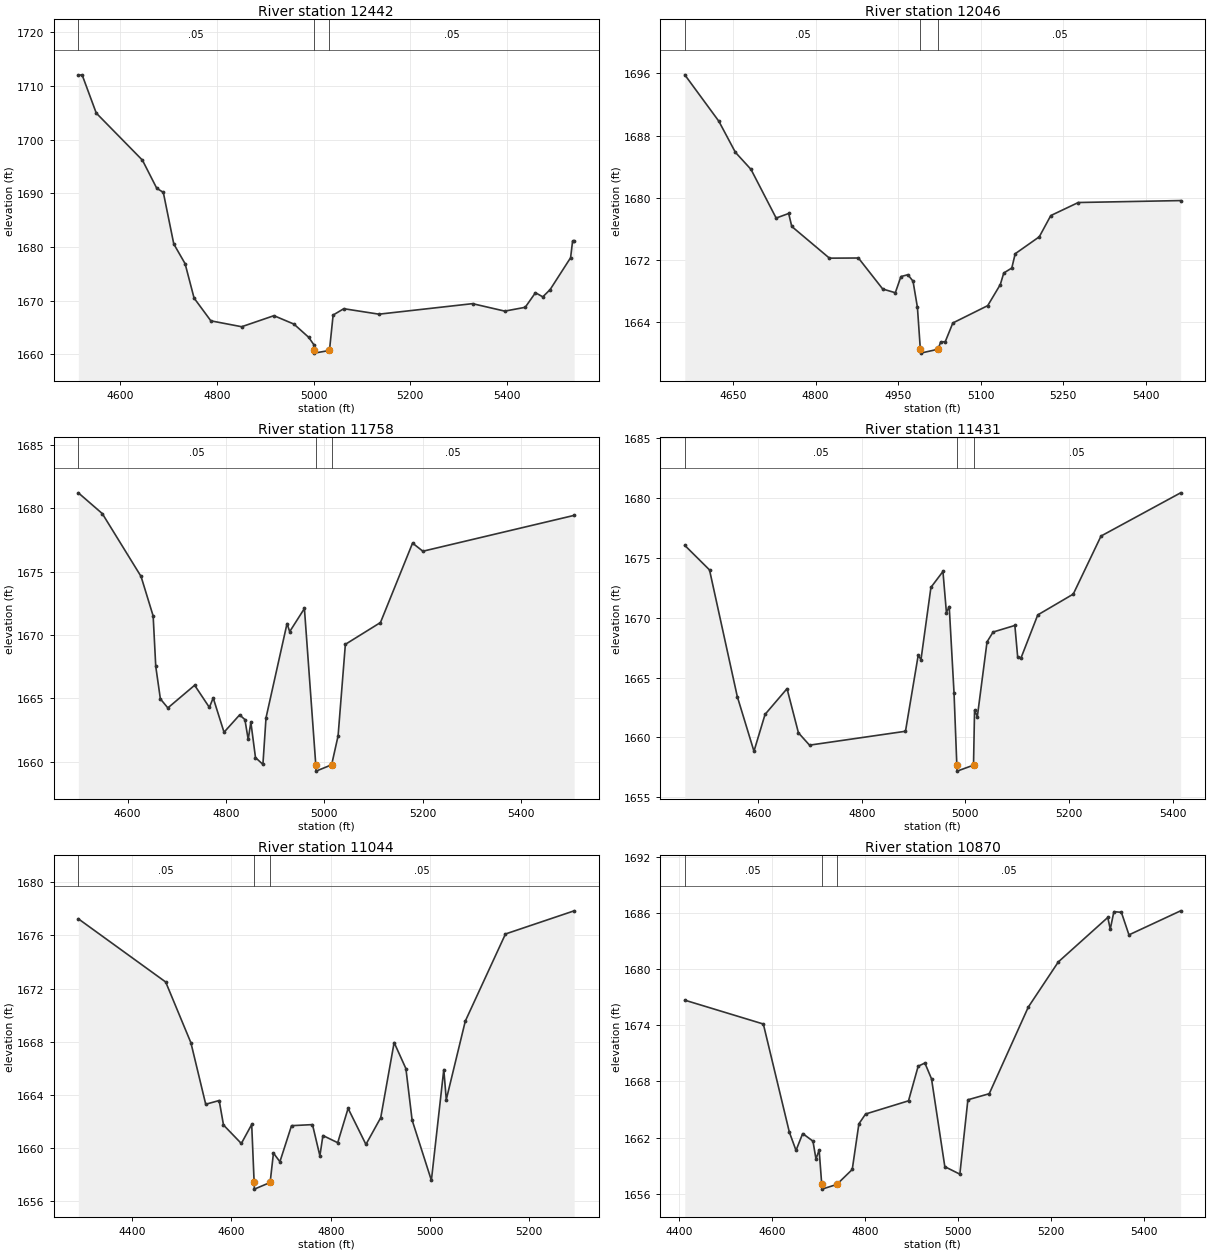
Type RM Length L Ch R = 1 ,12442   ,396,396,396
BEGIN DESCRIPTION:
Buck Creek 12442.45
END DESCRIPTION:
XS GIS Cut Line= 3
      1603802.31      6868540.26       1604255.9      6868726.91
      1604544.55      6869178.32
#Sta/Elev= 30
    4513 1712.01  4520.8  1712.1  4550.1 1704.97  4645.7 1696.19  4675.3 1690.96
  4688.9 1690.19  4710.6 1680.57    4734  1676.9  4752.6 1670.49  4787.3 1666.25
  4851.1 1665.15  4917.9 1667.21  4959.3 1665.64  4989.8 1663.18  5000.3 1661.82
  5000.8 1660.73  5001.3 1660.23  5032.8 1660.73  5040.4 1667.33  5062.5 1668.51
  5135.2 1667.49  5328.9 1669.45  5395.7 1668.06    5438 1668.77  5459.2 1671.49
  5474.4 1670.72  5489.6 1672.08  5531.9 1678.01  5536.1 1681.12  5539.3 1681.12
#Mann= 3 ,-1 , 0
    4513     .05       0  5000.8     .03       0  5032.8     .05       0
Bank Sta=5000.8,5032.8
XS Rating Curve= 0 ,0
Exp/Cntr=0.3,0.1

Type RM Length L Ch R = 1 ,12046   ,288,288,288
BEGIN DESCRIPTION:
Buck Creek 12149.885
END DESCRIPTION:
XS GIS Cut Line= 3
      1603618.96      6868842.96      1604015.61      6869028.25
      1604292.59      6869400.27
#Sta/Elev= 30
  4562.2 1695.81  4624.1 1689.84  4654.2 1685.84  4682.6 1683.64  4728.3 1677.38
  4751.1 1677.97  4756.7  1676.3  4825.2 1672.22  4877.9 1672.24  4922.1 1668.25
    4945 1667.77  4955.2 1669.85  4967.8 1670.09  4977.2 1669.26  4985.2 1665.89
  4990.5  1660.5  4991.1    1660  5022.7  1660.5  5027.5 1661.44  5035.8 1661.47
  5049.6 1663.88    5113 1666.11  5135.9 1668.82  5142.2 1670.31  5156.8 1670.95
    5163 1672.79  5206.8 1674.97  5227.7  1677.7  5277.7 1679.38  5463.8 1679.63
#Mann= 3 ,-1 , 0
  4562.2     .05       0  4990.5     .03       0  5022.7     .05       0
Bank Sta=4990.5,5022.7
XS Rating Curve= 0 ,0
Exp/Cntr=0.3,0.1

Type RM Length L Ch R = 1 ,11758   ,327,327,327
BEGIN DESCRIPTION:
Buck Creek 11758.08
END DESCRIPTION:
XS GIS Cut Line= 3
      1603489.61      6869117.44      1603958.39      6869299.74
      1604369.82      6869591.39
#Sta/Elev= 30
  4500.1 1681.22  4548.8 1679.58  4627.5 1674.62  4652.1  1671.5  4657.4 1667.51
  4666.8 1664.95    4682 1664.24  4736.4 1666.03  4766.3 1664.28  4774.1 1665.03
  4796.1 1662.32  4827.8 1663.69  4838.5 1663.32  4845.2 1661.75  4850.6 1663.11
    4860 1660.32  4875.1 1659.78  4881.4 1663.46  4924.1  1670.9  4929.5 1670.26
  4959.4 1672.09  4982.5 1659.75    4983 1659.25  5014.7 1659.75  5027.8 1662.03
  5042.6 1669.26  5113.9 1670.98  5179.1 1677.25  5200.1 1676.61  5507.4 1679.44
#Mann= 3 ,-1 , 0
  4500.1     .05       0  4982.5     .05       0  5014.7     .05       0
Bank Sta=4982.5,5014.7
XS Rating Curve= 0 ,0
Exp/Cntr=0.3,0.1

Type RM Length L Ch R = 1 ,11431   ,387,387,387
BEGIN DESCRIPTION:
Buck Creek 11430.97
END DESCRIPTION:
XS GIS Cut Line= 3
      1603450.54      6869429.94      1603960.99      6869627.87
      1604340.58      6869781.26
#Sta/Elev= 30
  4458.4 1676.05  4506.1    1674  4559.7 1663.42  4591.9 1658.85  4613.3 1661.93
  4655.7 1664.08  4677.7 1660.39  4699.1 1659.36  4884.3 1660.52  4908.9 1666.88
  4914.2  1666.5  4933.4 1672.54  4956.6 1673.87  4963.3 1670.44  4968.7 1670.94
    4978 1663.72  4983.4 1657.69  4983.9 1657.19  5015.6 1657.69  5017.6 1662.27
    5023 1661.75  5041.7 1667.99  5053.4 1668.81  5095.4 1669.36  5100.8 1666.73
  5107.3 1666.65  5139.6 1670.24  5208.1 1671.98  5261.7 1676.83  5415.3 1680.44
#Mann= 3 ,-1 , 0
  4458.4     .05       0  4983.4     .03       0  5015.6     .05       0
Bank Sta=4983.4,5015.6
XS Rating Curve= 0 ,0
Exp/Cntr=0.3,0.1

Type RM Length L Ch R = 1 ,11044   ,174,174,174
BEGIN DESCRIPTION:
Buck Creek 11574.93
END DESCRIPTION:
XS GIS Cut Line= 3
      1603281.34      6869575.81      1603864.73      6869977.31
       1604151.9      6869935.42
#Sta/Elev= 30
  4291.8 1677.25  4467.7  1672.5  4518.5 1667.93  4548.3 1663.31  4575.4 1663.59
  4584.1 1661.75    4620 1660.36  4640.9 1661.79  4645.8 1657.43  4646.3 1656.93
    4678 1657.43  4684.7 1659.64  4697.7 1658.99  4721.1  1661.7  4763.3 1661.78
  4778.2 1659.43  4784.3 1660.96  4814.1 1660.42    4835    1663  4870.9 1660.29
  4900.7  1662.3  4927.7 1667.95  4951.4 1665.99  4963.9 1662.12  5002.7 1657.59
  5027.7 1665.92  5032.7 1663.66    5071 1669.56  5151.9 1676.11  5290.2 1677.85
#Mann= 3 ,-1 , 0
  4291.8     .05       0  4645.8     .03       0    4678     .05       0
Bank Sta=4645.8,4678
XS Rating Curve= 0 ,0
Exp/Cntr=0.3,0.1

Type RM Length L Ch R = 1 ,10870   ,446,446,446
BEGIN DESCRIPTION:
Buck Creek 10869.67
END DESCRIPTION:
XS GIS Cut Line= 3
      1603273.69      6869691.87      1603726.84       6870072.1
      1603908.88      6870510.57
#Sta/Elev= 30
  4412.5 1676.69  4581.4 1674.14  4637.4 1662.57  4651.7 1660.63    4666 1662.43
  4688.1 1661.62  4694.6 1659.71  4701.4 1660.68    4707 1656.99  4707.5 1656.49
  4739.4 1656.99  4772.6 1658.59  4786.9 1663.47  4801.3 1664.52  4893.6 1665.93
  4914.4 1669.63  4928.8 1669.97  4943.1 1668.28  4971.7 1658.89    5004 1658.09
  5021.3 1666.04  5067.2 1666.69  5151.2 1675.95  5215.8 1680.78  5322.1 1685.53
  5327.5 1684.29  5335.3 1686.15  5351.4 1686.08  5367.7 1683.67  5478.8 1686.24
#Mann= 3 ,-1 , 0
  4412.5     .05       0    4707     .05       0  4739.4     .05       0
Bank Sta=4707,4739.4
XS Rating Curve= 0 ,0
Exp/Cntr=0.3,0.1

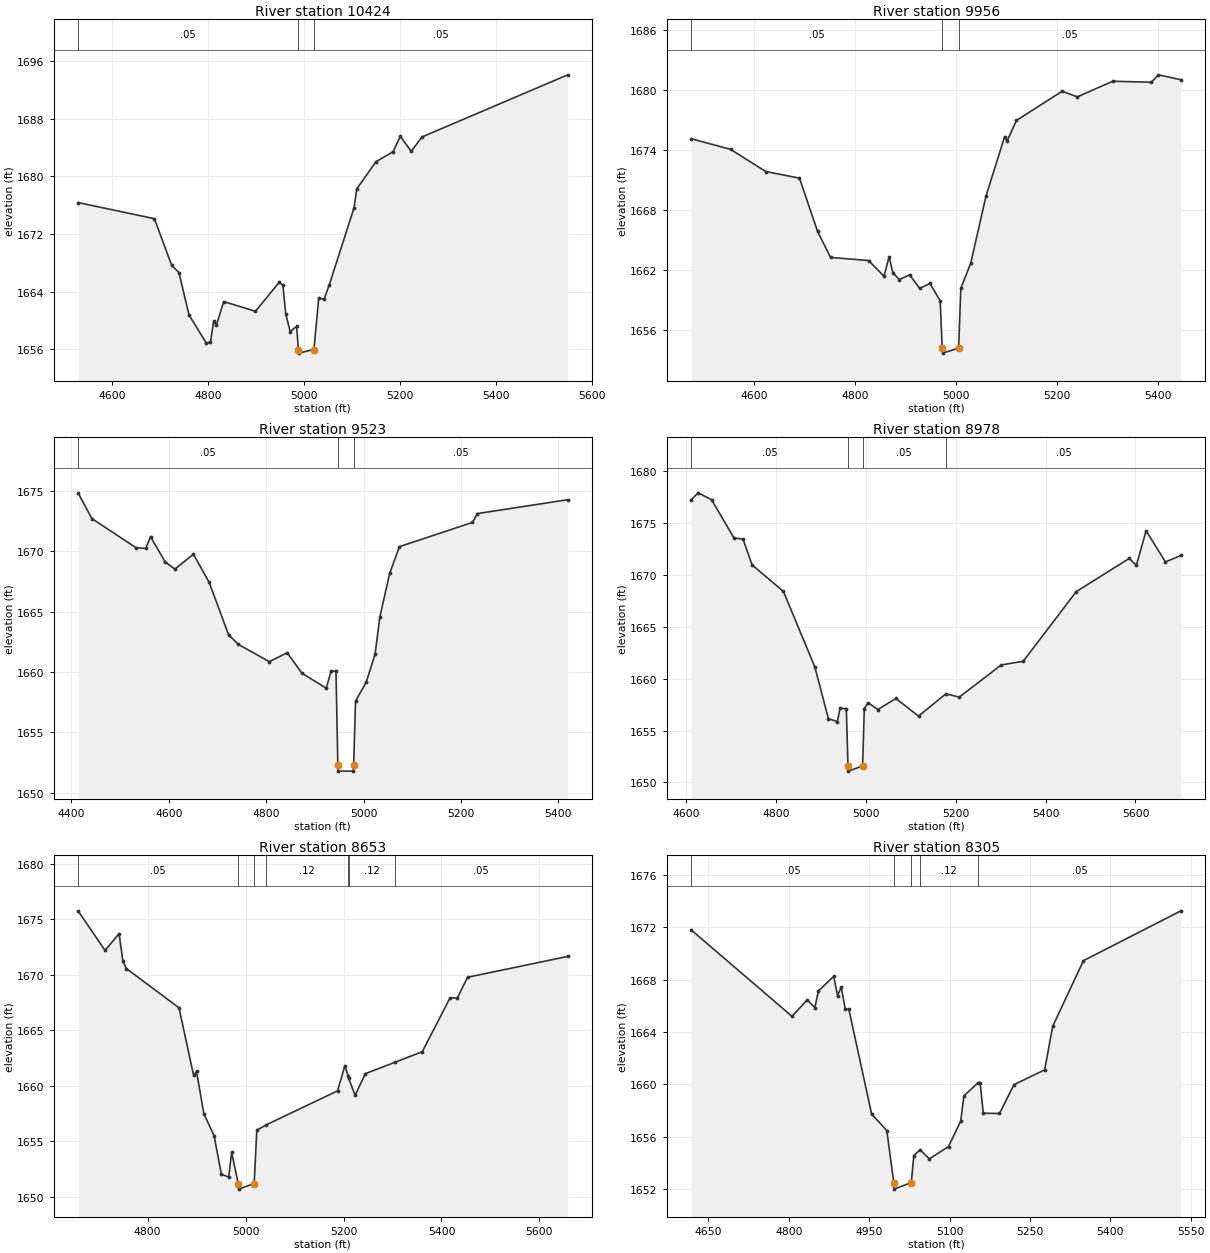
Type RM Length L Ch R = 1 ,10424   ,468,468,468
BEGIN DESCRIPTION:
Buck Creek 10424.14
END DESCRIPTION:
XS GIS Cut Line= 3
      1603094.01      6869897.59      1603357.04      6870296.05
      1603590.69      6870786.71
#Sta/Elev= 30
  4528.6 1676.36  4687.8 1674.12  4723.9 1667.65    4739 1666.66    4760 1660.78
  4796.1 1656.85  4804.7 1656.99  4811.2 1659.87  4817.2 1659.38  4832.3 1662.63
  4898.5 1661.28  4948.5 1665.35  4955.7 1664.86  4961.7 1660.93  4970.8 1658.46
  4984.4 1659.19    4988 1655.98  4988.5 1655.48  5020.4 1655.98  5030.4 1663.11
  5041.6 1662.98  5052.5 1664.97  5104.2 1675.67  5109.7 1678.25  5149.6 1682.02
  5185.4 1683.41  5200.5 1685.54  5223.2 1683.46  5245.9 1685.46  5549.5 1694.07
#Mann= 3 ,-1 , 0
  4528.6     .05       0    4988     .05       0  5020.4     .05       0
Bank Sta=4988,5020.4
XS Rating Curve= 0 ,0
Exp/Cntr=0.3,0.1

Type RM Length L Ch R = 1 ,9956    ,433,433,433
BEGIN DESCRIPTION:
Buck Creek 9956.4
END DESCRIPTION:
XS GIS Cut Line= 3
      1602875.79      6869970.94      1602960.41       6870493.9
      1603005.99      6870932.28
#Sta/Elev= 30
  4475.5 1675.14  4553.6 1674.07  4623.2 1671.86    4690  1671.2  4725.8 1665.89
  4751.7 1663.28  4827.1 1662.97  4857.5  1661.4  4867.6 1663.34  4875.1 1661.76
  4887.9 1661.06  4908.1 1661.55  4928.4 1660.19  4948.6 1660.68  4968.9 1658.94
  4972.9 1654.22  4973.5 1653.72  5005.4 1654.22  5009.8 1660.18  5029.5 1662.72
  5059.7 1669.41  5096.4 1675.32  5101.4 1674.91    5120 1676.96  5210.5 1679.88
  5240.6 1679.32    5311 1680.88  5387.2 1680.78  5401.5 1681.52    5446 1681.03
#Mann= 3 ,-1 , 0
  4475.5     .05       0  4972.9     .05       0  5005.4     .05       0
Bank Sta=4972.9,5005.4
XS Rating Curve= 0 ,0
Exp/Cntr=0.3,0.1

Type RM Length L Ch R = 1 ,9523    ,545,545,545
BEGIN DESCRIPTION:
Buck Creek 9522.5
END DESCRIPTION:
XS GIS Cut Line= 3
      1602595.83      6869799.43      1602556.77      6870389.73
      1602552.44      6870803.62
#Sta/Elev= 30
  4413.6 1674.84  4442.2  1672.7  4532.4  1670.3  4552.5 1670.23  4562.5 1671.21
  4592.6 1669.11  4612.6 1668.52  4650.5 1669.76  4682.8 1667.43  4722.8 1663.07
  4742.9 1662.28  4806.4 1660.85  4843.1 1661.59  4873.2  1659.9  4923.3 1658.65
  4933.3 1660.08  4943.3 1660.05  4947.1 1652.28  4947.7 1651.78  4979.1 1651.78
  4979.6 1652.28  4983.4 1657.59  5005.2 1659.13  5023.5 1661.47  5033.5 1664.59
  5053.5 1668.16  5073.5 1670.38  5223.5 1672.39  5233.5 1673.12  5419.1 1674.27
#Mann= 3 ,-1 , 0
  4413.6     .05       0  4947.1     .05       0  4979.6     .05       0
Bank Sta=4947.1,4979.6
XS Rating Curve= 0 ,0
Exp/Cntr=0.3,0.1

Type RM Length L Ch R = 1 ,8978    ,325,325,325
BEGIN DESCRIPTION:
Buck Creek 8978.17
END DESCRIPTION:
XS GIS Cut Line= 4
      1602229.08      6869662.74      1602218.23      6870059.87
      1602187.85      6870309.44      1602406.86      6870693.26
#Sta/Elev= 30
  4610.6 1677.23  4625.9  1677.9  4655.9 1677.24  4705.9 1673.54  4725.9 1673.45
  4745.9 1670.97  4815.9  1668.4    4886 1661.11    4916 1656.15    4936 1655.85
    4942 1657.15    4956 1657.11  4959.7 1651.59  4960.2 1651.09  4992.3 1651.59
    4996 1657.11  5004.4 1657.68  5026.1 1657.02  5066.4 1658.09  5116.8 1656.39
  5177.8 1658.54  5207.5 1658.22    5301 1661.32  5349.9 1661.67    5468 1668.38
  5586.1 1671.58    5602 1670.91  5623.6 1674.25  5666.8 1671.24  5701.2 1671.87
#Mann= 4 ,-1 , 0
  4610.6     .05       0  4959.7     .07       0  4992.3     .05       0
  5177.8     .05       0
Bank Sta=4959.7,4992.3
XS Rating Curve= 0 ,0
Exp/Cntr=0.3,0.1

Type RM Length L Ch R = 1 ,8653    ,348,348,348
BEGIN DESCRIPTION:
Buck Creek 8653.26
END DESCRIPTION:
XS GIS Cut Line= 3
      1601699.58      6870016.48      1601986.02      6870213.95
      1602357.14      6870750.01
#Sta/Elev= 30
  4657.9 1675.78  4713.1 1672.21  4741.7 1673.72  4749.5 1671.26  4756.5 1670.58
    4864 1667.04  4893.8 1660.97  4899.9  1661.3  4914.8 1657.49  4935.7 1655.51
  4950.6 1652.03  4965.5 1651.78  4971.6    1654    4985 1651.19  4985.6 1650.69
  5017.6 1651.19  5022.9    1656  5042.4 1656.49  5187.8 1659.55  5202.7 1661.81
  5209.6 1660.89  5210.6 1660.67  5223.6 1659.15  5244.6  1661.1  5304.7 1662.12
  5360.8 1663.08  5417.5 1667.93  5432.4 1667.92  5453.3 1669.79  5657.8 1671.67
#Mann= 7 ,-1 , 0
  4657.9     .05       0    4985     .05       0  5017.6     .05       0
  5042.4     .12       0  5209.6     .05       0  5210.6     .12       0
  5304.7     .05       0
Bank Sta=4985,5017.6
XS Rating Curve= 0 ,0
Exp/Cntr=0.3,0.1

Type RM Length L Ch R = 1 ,8305    ,513,513,513
BEGIN DESCRIPTION:
Buck Creek 8305.14
END DESCRIPTION:
XS GIS Cut Line= 3
      1601651.94      6870255.29      1601910.65      6870534.84
      1602202.29      6870980.98
#Sta/Elev= 30
  4617.9 1671.78    4806 1665.19  4834.3 1666.45  4848.5 1665.86  4855.3 1667.13
  4883.7 1668.24    4891 1666.77  4897.8 1667.43  4905.2 1665.76    4912 1665.74
  4954.5 1657.74  4982.9 1656.48  4995.9 1652.51  4996.4 1652.01  5028.6 1652.51
  5033.3 1654.57  5044.9 1655.02  5062.3 1654.32  5098.1 1655.26  5120.8  1657.2
  5126.8 1659.12  5153.1 1660.13    5157 1660.14    5163  1657.8  5193.2 1657.78
  5220.3 1659.98  5277.5 1661.11  5292.6 1664.44  5349.9 1669.44  5531.8 1673.24
#Mann= 5 ,-1 , 0
  4617.9     .05       0  4995.9     .05       0  5028.6     .05       0
  5044.9     .12       0  5153.1     .05       0
Bank Sta=4995.9,5028.6
XS Rating Curve= 0 ,0
Exp/Cntr=0.3,0.1