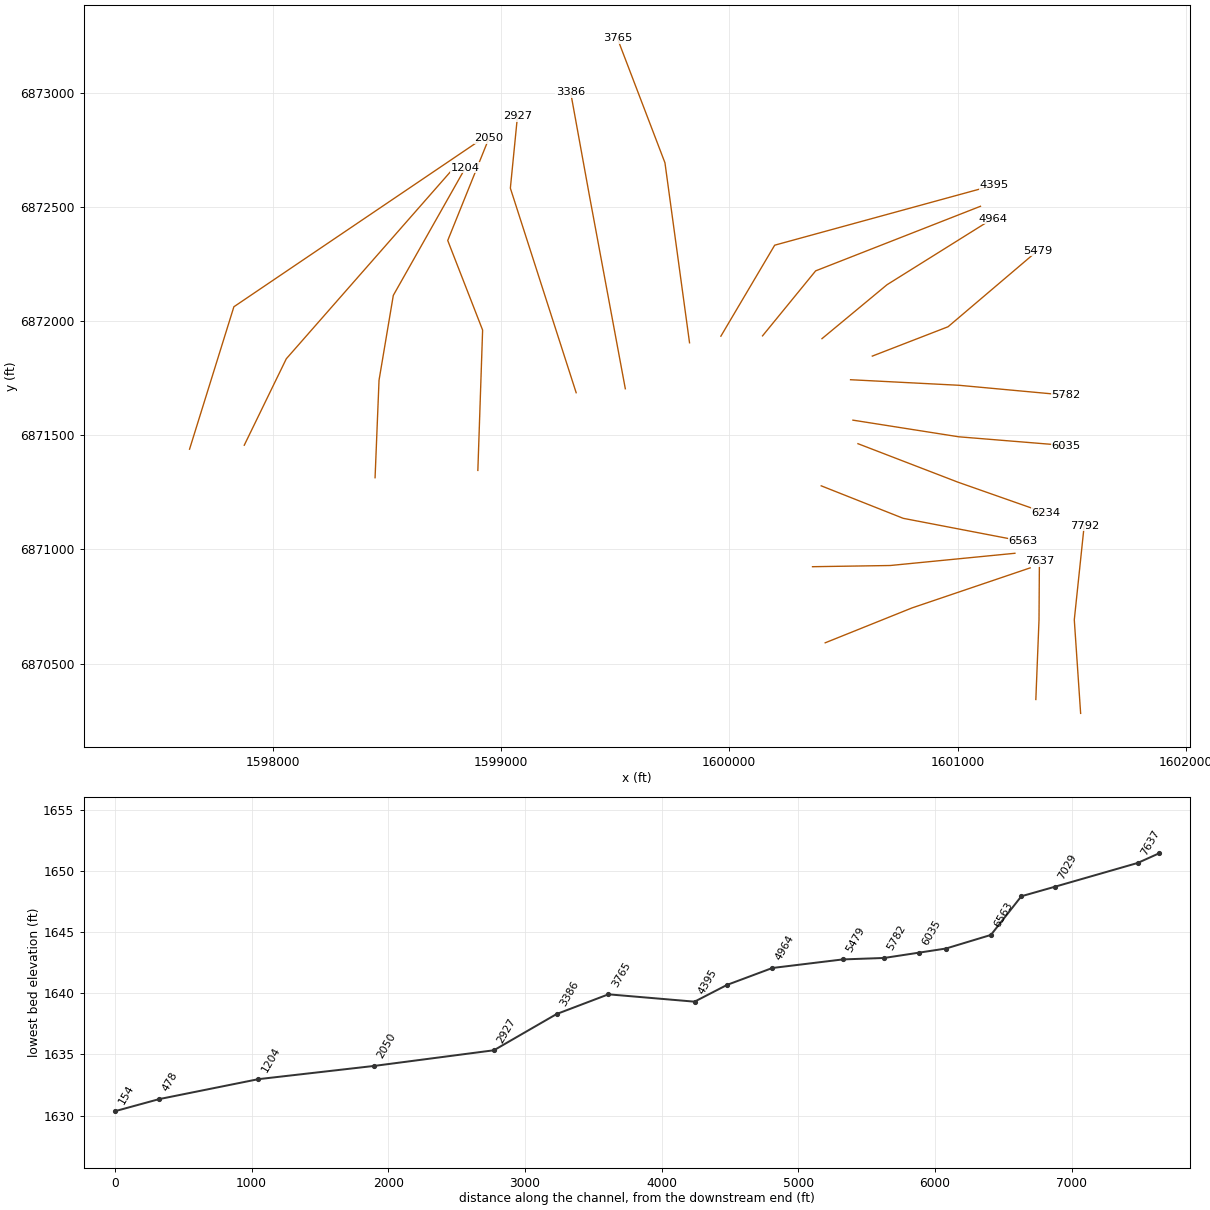
HEC-RAS study Buck Creek.prj: Buck Creek Base Level Engineering

--- Buck Creek.g01 (geometry) --- (continued)

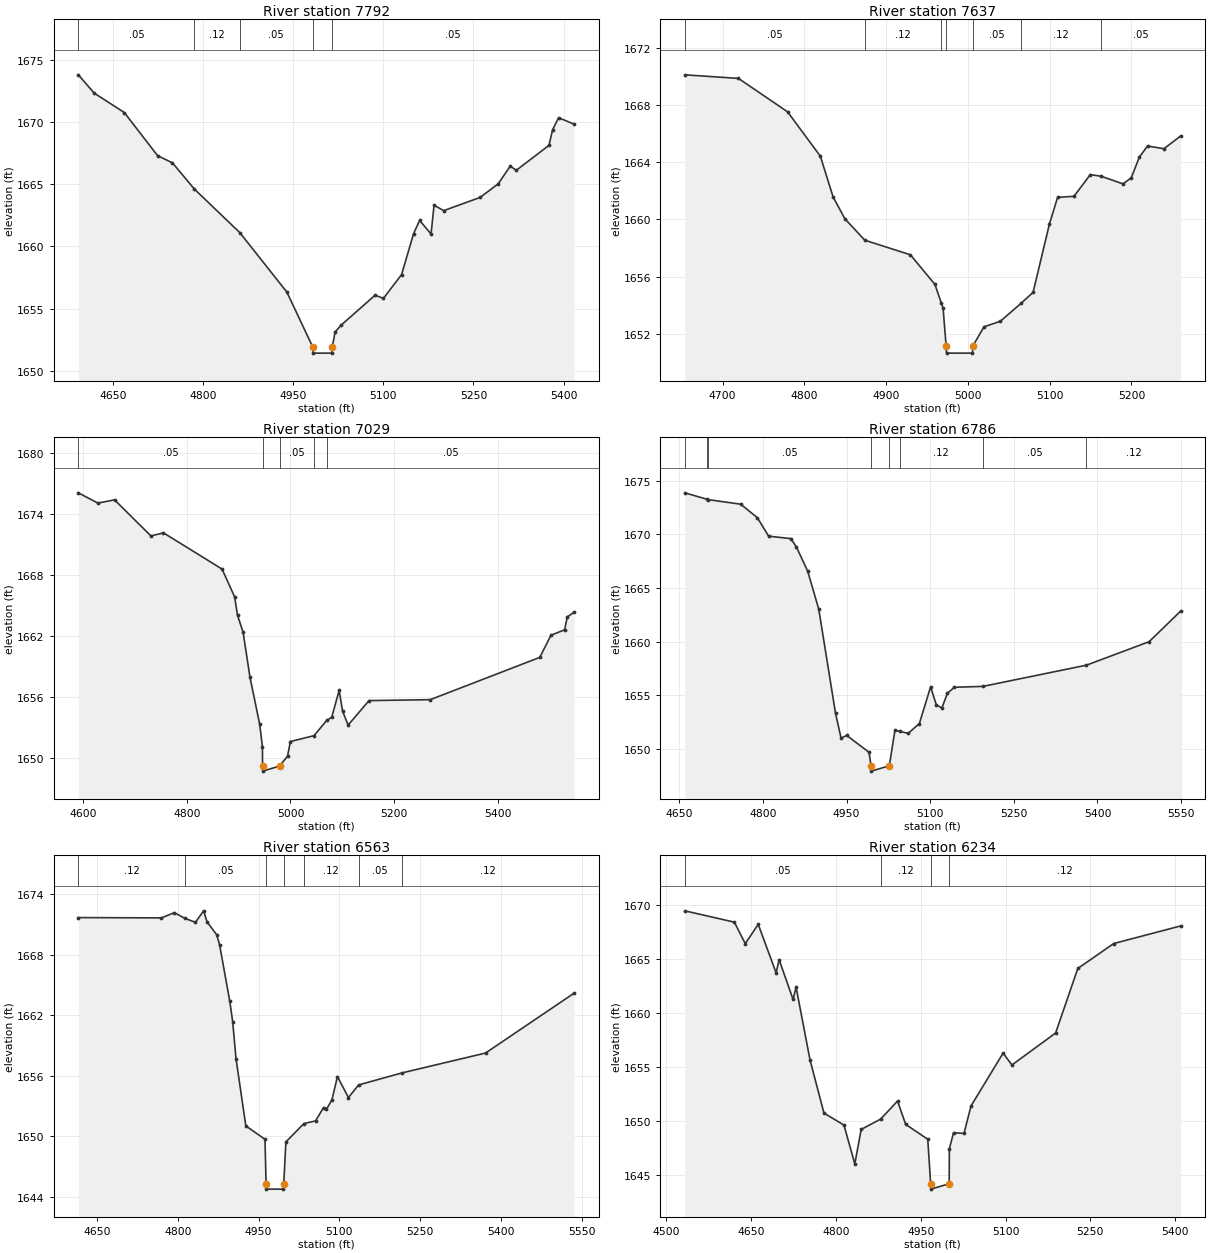
Type RM Length L Ch R = 1 ,7792    ,155,155,155
BEGIN DESCRIPTION:
Buck Creek 7792.04
END DESCRIPTION:
XS GIS Cut Line= 3
      1601538.95      6870281.69      1601511.17      6870691.44
      1601554.48      6871103.78
#Sta/Elev= 30
  4592.4  1673.8  4618.8 1672.33  4668.9 1670.77  4724.3  1667.3  4749.1 1666.72
  4785.6 1664.61  4861.2 1661.11  4939.5 1656.33  4982.5 1651.92  4983.1 1651.42
  5014.7 1651.42  5015.2 1651.92  5019.7 1653.11  5029.8 1653.67  5086.4 1656.08
  5100.2 1655.82  5130.4 1657.73  5150.5 1661.04  5160.5 1662.09  5179.5    1661
  5184.5 1663.31  5200.7 1662.88  5261.1 1663.94  5291.2 1665.03  5311.3 1666.46
  5321.4 1666.12  5375.8 1668.13  5381.7 1669.37  5391.8 1670.35  5417.7 1669.83
#Mann= 5 ,-1 , 0
  4592.4     .05       0  4785.6     .12       0  4861.2     .05       0
  4982.5     .03       0  5015.2     .05       0
Bank Sta=4982.5,5015.2
XS Rating Curve= 0 ,0
Exp/Cntr=0.3,0.1

Type RM Length L Ch R = 1 ,7637    ,608,608,608
BEGIN DESCRIPTION:
Buck Creek 7637.19
END DESCRIPTION:
XS GIS Cut Line= 3
      1601342.76      6870342.44      1601356.65      6870691.44
      1601358.39      6870948.36
#Sta/Elev= 30
  4653.9 1670.11  4719.5 1669.86  4779.6 1667.52  4819.6 1664.42  4835.2 1661.57
  4849.6 1660.04    4874 1658.54  4929.7 1657.52  4959.7 1655.45  4967.3 1654.18
  4969.7 1653.78  4973.4 1651.14  4973.9 1650.64  5005.5 1650.64  5006.1 1651.14
  5019.7 1652.48  5039.7 1652.87  5065.3 1654.14  5079.7 1654.89  5099.7 1659.67
  5109.7 1661.54  5129.7 1661.61  5149.7 1663.13  5163.2 1663.01  5189.7 1662.48
  5199.7  1662.9  5209.7 1664.36  5219.7 1665.13  5239.7 1664.94  5260.1 1665.83
#Mann= 7 ,-1 , 0
  4653.9     .05       0    4874     .12       0  4967.3     .05       0
  4973.4     .05       0  5006.1     .05       0  5065.3     .12       0
  5163.2     .05       0
Bank Sta=4973.4,5006.1
XS Rating Curve= 0 ,0
Exp/Cntr=0.3,0.1

Type RM Length L Ch R = 1 ,7029    ,243,243,243
BEGIN DESCRIPTION:
Buck Creek 7029.38
END DESCRIPTION:
XS GIS Cut Line= 3
      1600420.23      6870590.76       1600800.4      6870743.52
      1601317.78      6870918.87
#Sta/Elev= 30
    4591 1676.07  4628.8 1675.06  4660.8 1675.38    4731 1671.83  4755.2 1672.13
  4868.1 1668.57  4892.3 1665.84  4897.9 1664.03  4908.7 1662.35  4921.9 1657.94
  4940.6 1653.32    4946 1651.09  4946.2 1649.19  4946.7 1648.69    4979 1649.19
  4994.4 1650.16  4999.8  1651.6  5045.3 1652.18  5070.2 1653.69  5079.5 1653.98
  5093.9 1656.63  5100.6 1654.57  5111.2 1653.22  5151.5 1655.63  5269.5 1655.72
  5480.7 1659.88  5502.3 1662.06  5528.5 1662.59  5533.7 1663.85    5547 1664.34
#Mann= 5 ,-1 , 0
    4591     .05       0  4946.2     .05       0    4979     .05       0
  5045.3     .12       0  5070.2     .05       0
Bank Sta=4946.2,4979
XS Rating Curve= 0 ,0
Exp/Cntr=0.3,0.1

Type RM Length L Ch R = 1 ,6786    ,223,223,223
BEGIN DESCRIPTION:
Buck Creek 6786.48
END DESCRIPTION:
XS GIS Cut Line= 3
      1600364.68      6870924.08      1600704.92      6870929.29
      1601251.22      6870982.88
#Sta/Elev= 30
  4659.9 1673.87    4699 1673.28  4701.2 1673.24  4760.2 1672.81  4790.2 1671.54
  4810.2 1669.83  4850.2  1669.6  4860.2  1668.8  4880.2 1666.58  4900.2 1663.01
  4930.2 1653.31  4940.2 1650.99  4950.2 1651.25  4990.3 1649.68  4993.9 1648.42
  4994.5 1647.92  5026.7 1648.42  5036.8 1651.74  5045.1 1651.63  5060.5 1651.44
  5080.6 1652.36  5100.7 1655.78  5110.8 1654.12  5120.8  1653.8  5130.9 1655.18
  5143.3 1655.74  5194.3 1655.82  5380.2  1657.8  5492.6 1659.99  5549.1 1662.84
#Mann= 8 ,-1 , 0
  4659.9     .05       0    4699     .12       0  4701.2     .05       0
  4993.9     .05       0  5026.7     .05       0  5045.1     .12       0
  5194.3     .05       0  5380.2     .12       0
Bank Sta=4993.9,5026.7
XS Rating Curve= 0 ,0
Exp/Cntr=0.3,0.1

Type RM Length L Ch R = 1 ,6563    ,329,329,329
BEGIN DESCRIPTION:
Buck Creek 6563.25
END DESCRIPTION:
XS GIS Cut Line= 3
      1600402.88      6871278.23      1600762.21      6871135.88
      1601286.53      6871035.19
#Sta/Elev= 30
  4615.5 1671.68  4769.6 1671.65  4793.9 1672.17    4813 1671.61  4832.9 1671.21
    4848 1672.35  4854.4 1671.26  4872.3 1669.98  4877.7 1668.99  4896.6  1663.4
    4902 1661.37  4908.2  1657.7  4926.4 1651.03    4962  1649.7    4964 1645.26
  4964.5 1644.76  4996.2 1644.76  4996.8 1645.26  5000.8 1649.44  5034.3 1651.26
  5055.8 1651.52  5070.7 1652.85  5076.1 1652.67  5086.3 1653.62  5096.5 1655.92
  5116.9 1653.84  5135.8 1655.09  5216.1 1656.28  5371.4 1658.25  5535.9 1664.19
#Mann= 7 ,-1 , 0
  4615.5     .12       0    4813     .05       0    4964     .05       0
  4996.8     .05       0  5034.3     .12       0  5135.8     .05       0
  5216.1     .12       0
Bank Sta=4964,4996.8
XS Rating Curve= 0 ,0
Exp/Cntr=0.3,0.1

Type RM Length L Ch R = 1 ,6234    ,199,199,199
BEGIN DESCRIPTION:
Buck Creek 6234.1
END DESCRIPTION:
XS GIS Cut Line= 3
      1600563.75       6871462.8      1601001.27      6871294.39
      1601386.66      6871158.98
#Sta/Elev= 30
  4532.5 1669.43  4620.2 1668.38  4639.5 1666.39  4662.4 1668.18  4694.1 1663.68
  4699.4  1664.9  4724.1 1661.22  4729.4 1662.36  4754.1 1655.61  4778.7  1650.7
  4814.1 1649.58  4833.3 1645.99  4844.6 1649.18  4879.1 1650.14  4908.9 1651.81
  4923.3 1649.65  4962.4 1648.27  4967.5 1644.15    4968 1643.65  5000.3 1644.15
  5000.6 1647.38    5008 1648.88  5026.5 1648.81    5039 1651.36  5095.7 1656.25
  5111.3 1655.15  5188.6 1658.11  5227.9 1664.09  5291.4  1666.4  5409.8 1668.03
#Mann= 4 ,-1 , 0
  4532.5     .05       0  4879.1     .12       0  4967.5     .07       0
  5000.3     .12       0
Bank Sta=4967.5,5000.3
XS Rating Curve= 0 ,0
Exp/Cntr=0.3,0.1

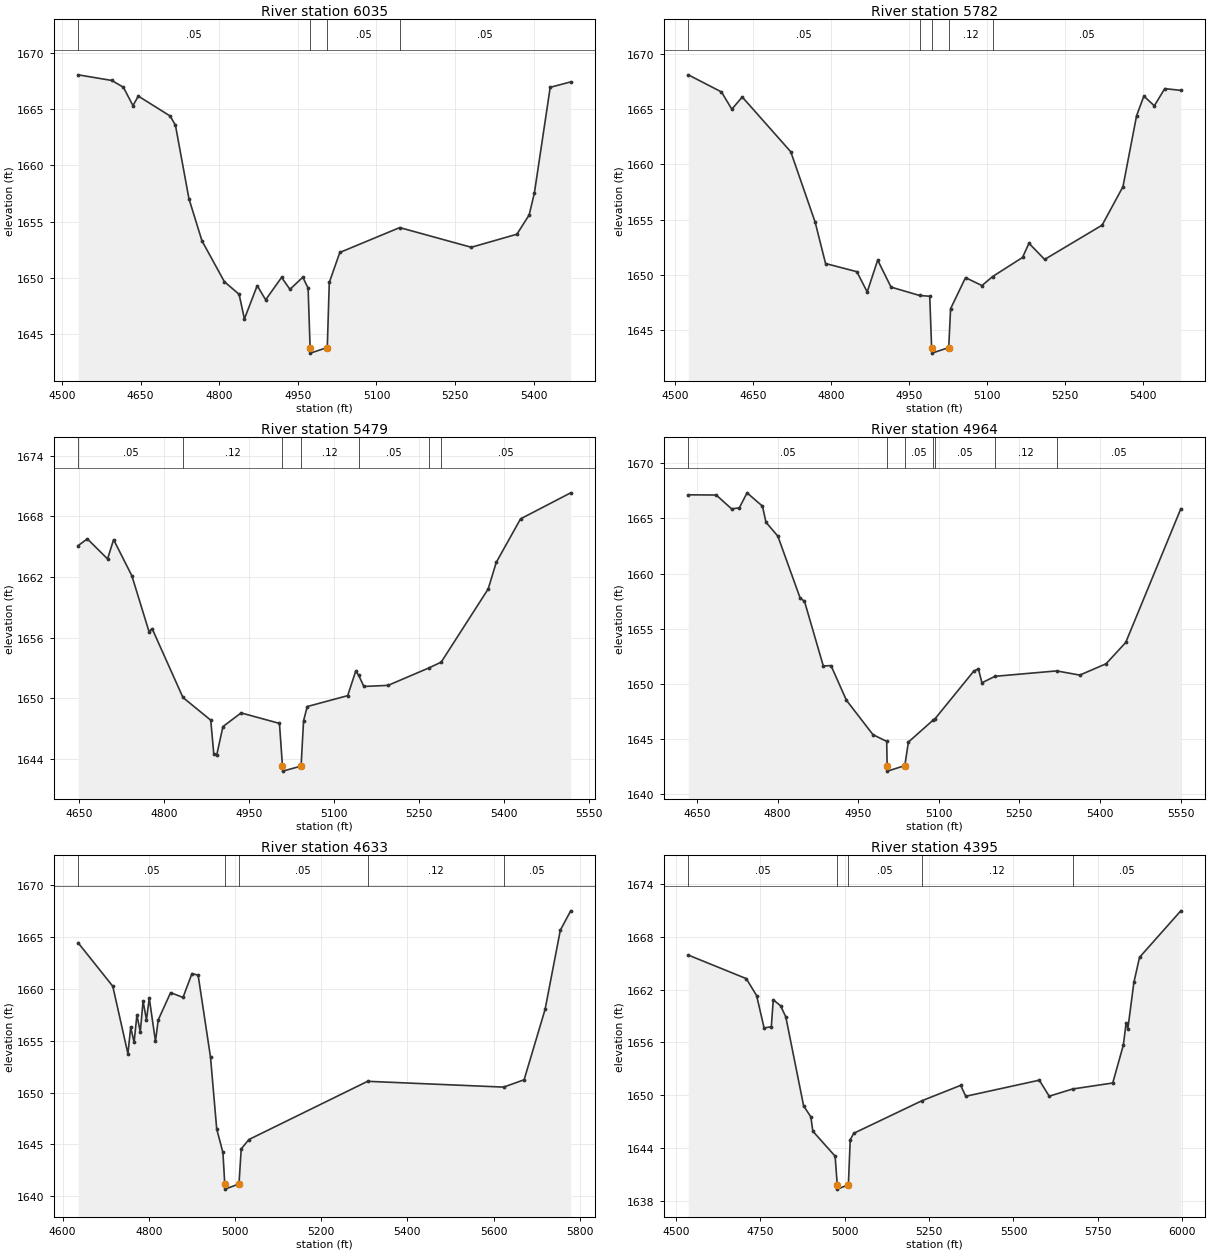
Type RM Length L Ch R = 1 ,6035    ,253,253,253
BEGIN DESCRIPTION:
Buck Creek 6034.76
END DESCRIPTION:
XS GIS Cut Line= 3
      1600541.73      6871565.92      1601005.26        6871493.
      1601473.98      6871454.81
#Sta/Elev= 30
    4531 1668.05    4595 1667.55  4617.2 1666.95  4635.5 1665.31  4645.7 1666.16
  4706.4 1664.39  4716.5 1663.58  4742.3 1657.04  4767.1  1653.3  4809.9 1649.66
    4838 1648.54  4848.1 1646.35  4872.5 1649.31  4888.6 1648.05    4919 1650.04
    4935 1648.98  4959.5 1650.06  4969.6 1649.09  4973.4 1643.81    4974 1643.31
  5006.2 1643.81    5010 1649.59  5030.1 1652.26  5144.4 1654.47  5280.9 1652.72
  5367.9 1653.88  5391.3  1655.6  5401.3 1657.56  5431.4 1666.94  5470.5 1667.42
#Mann= 4 ,-1 , 0
    4531     .05       0  4973.4     .07       0  5006.2     .05       0
  5144.4     .05       0
Bank Sta=4973.4,5006.2
XS Rating Curve= 0 ,0
Exp/Cntr=0.3,0.1

Type RM Length L Ch R = 1 ,5782    ,303,303,303
BEGIN DESCRIPTION:
Buck Creek 5782.08
END DESCRIPTION:
XS GIS Cut Line= 3
      1600531.32        6871743.      1601005.26       6871718.7
       1601475.7       6871675.3
#Sta/Elev= 30
    4525 1668.13  4588.8 1666.58  4608.8 1665.01  4628.8 1666.12  4722.1 1661.15
    4769 1654.76    4789 1651.01  4849.1 1650.27  4869.1 1648.43  4889.2 1651.32
  4914.9 1648.87  4969.8 1648.11  4989.3 1648.04  4992.9 1643.38  4993.5 1642.88
  5025.8 1643.38  5029.4 1646.91  5058.1 1649.73  5089.7 1649.01  5110.3 1649.83
  5167.7 1651.56  5180.1 1652.85  5210.2 1651.38  5320.7 1654.49  5360.8 1657.98
    5387 1664.42    5401  1666.2  5421.1 1665.32  5441.2 1666.88    5472 1666.72
#Mann= 5 ,-1 , 0
    4525     .05       0  4969.8     .12       0  4992.9     .07       0
  5025.8     .12       0  5110.3     .05       0
Bank Sta=4992.9,5025.8
XS Rating Curve= 0 ,0
Exp/Cntr=0.3,0.1

Type RM Length L Ch R = 1 ,5479    ,515,515,515
BEGIN DESCRIPTION:
Buck Creek 5478.56
END DESCRIPTION:
XS GIS Cut Line= 3
       1600626.6      6871846.47      1600958.22      6871974.95
      1601350.29      6872308.04
#Sta/Elev= 30
  4647.9 1665.11  4664.1 1665.78  4699.8 1663.79  4710.5  1665.7  4742.7 1662.13
  4773.1 1656.58  4778.5 1656.89    4833 1650.06  4882.1 1647.81  4887.5 1644.46
  4892.8 1644.39  4903.6 1647.17  4935.7 1648.53  5003.5 1647.49  5008.8 1643.26
  5009.3 1642.76  5041.7 1643.26  5046.1 1647.76  5052.6 1649.16    5124 1650.24
  5138.3 1652.68  5143.5 1652.25  5152.6 1651.15  5195.4 1651.26  5267.2 1652.98
  5289.2 1653.56  5372.2 1660.81  5386.5 1663.45  5429.4 1667.76    5518 1670.34
#Mann= 7 ,-1 , 0
  4647.9     .05       0    4833     .12       0  5008.8     .07       0
  5041.7     .12       0  5143.5     .05       0  5267.2     .12       0
  5289.2     .05       0
Bank Sta=5008.8,5041.7
XS Rating Curve= 0 ,0
Exp/Cntr=0.3,0.1

Type RM Length L Ch R = 1 ,4964    ,331,331,331
BEGIN DESCRIPTION:
Buck Creek 4964.21
END DESCRIPTION:
XS GIS Cut Line= 3
      1600406.15      6871922.87      1600690.85      6872158.97
      1601154.38       6872448.9
#Sta/Elev= 30
  4633.9 1667.15    4686 1667.13  4714.6 1665.87    4729 1665.97  4743.3 1667.33
    4772 1666.12  4778.5 1664.66  4800.6  1663.4  4842.3 1657.75  4850.1  1657.5
  4885.2 1651.61  4899.6 1651.64  4928.2  1648.5  4977.7 1645.37  5003.2 1644.76
    5004 1642.56  5004.6 1642.06  5036.9 1642.56  5043.6  1644.7    5090 1646.71
  5092.7 1646.79  5165.1 1651.13  5173.8 1651.36  5180.4 1650.08  5204.8 1650.67
  5319.6 1651.16  5362.5 1650.78  5411.5 1651.81    5448 1653.74  5550.5 1665.88
#Mann= 7 ,-1 , 0
  4633.9     .05       0    5004     .05       0  5036.9     .05       0
    5090     .12       0  5092.7     .05       0  5204.8     .12       0
  5319.6     .05       0
Bank Sta=5004,5036.9
XS Rating Curve= 0 ,0
Exp/Cntr=0.3,0.1

Type RM Length L Ch R = 1 ,4633    ,238,238,238
BEGIN DESCRIPTION:
Buck Creek 4632.93
END DESCRIPTION:
XS GIS Cut Line= 3
      1600145.75      6871935.05      1600378.35      6872219.74
      1601100.28      6872502.61
#Sta/Elev= 30
  4636.1 1664.46  4716.4 1660.27  4751.6 1653.75    4758 1656.31  4765.9 1654.85
  4772.4 1657.49  4780.3 1655.86  4786.7 1658.84  4794.6 1657.03  4801.1 1659.12
  4815.5 1654.95  4821.9 1657.02  4850.6 1659.65  4879.4 1659.19  4900.2 1661.49
  4914.5 1661.34  4943.2 1653.43  4957.6 1646.49    4972 1644.22  4976.3 1641.18
  4976.9 1640.68  5009.3 1641.18  5014.5 1644.57  5032.4 1645.47  5307.8 1651.09
  5623.4 1650.53    5671 1651.24  5719.7 1658.04    5755 1665.68  5779.1 1667.55
#Mann= 5 ,-1 , 0
  4636.1     .05       0  4976.3     .05       0  5009.3     .05       0
  5307.8     .12       0  5623.4     .05       0
Bank Sta=4976.3,5009.3
XS Rating Curve= 0 ,0
Exp/Cntr=0.3,0.1

Type RM Length L Ch R = 1 ,4395    ,630,630,630
BEGIN DESCRIPTION:
Buck Creek 4617.62
END DESCRIPTION:
XS GIS Cut Line= 3
      1599963.36      6871933.77        1600199.       6872332.2
      1601158.99      6872594.95
#Sta/Elev= 30
  4537.1 1665.93  4708.9 1663.25  4739.5 1661.32  4761.6 1657.64    4783 1657.78
  4788.8 1660.84  4810.3 1660.17  4825.9  1658.9  4878.6 1648.79  4900.1 1647.52
  4905.9  1645.9  4971.9 1643.06  4978.2 1639.81  4978.8 1639.31  5011.2 1639.81
  5016.6 1644.92    5027 1645.66  5228.7 1649.36  5343.6 1651.11  5358.7 1649.87
  5576.4  1651.7  5605.7 1649.88  5675.2  1650.7  5793.8 1651.38  5825.3  1655.7
  5833.4  1658.2  5838.6 1657.56  5856.4 1662.81  5873.1 1665.67  5995.3 1670.96
#Mann= 5 ,-1 , 0
  4537.1     .05       0  4978.2     .05       0  5011.2     .05       0
  5228.7     .12       0  5675.2     .05       0
Bank Sta=4978.2,5011.2
XS Rating Curve= 0 ,0
Exp/Cntr=0.3,0.1

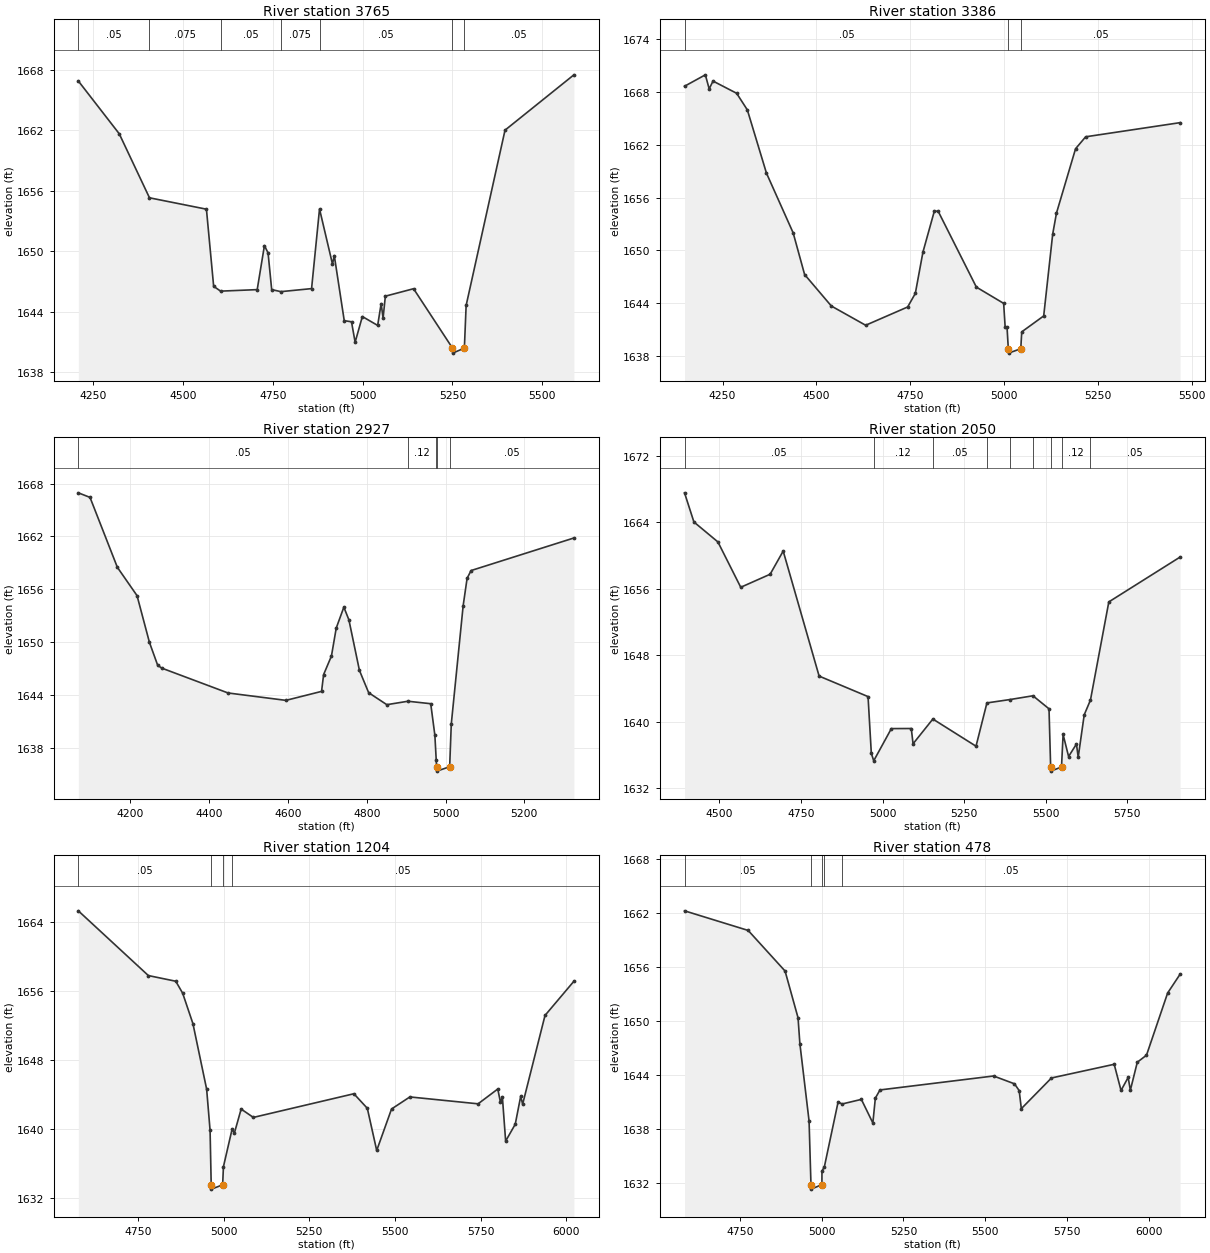
Type RM Length L Ch R = 1 ,3765    ,379,379,379
BEGIN DESCRIPTION:
Buck Creek 3764.75
END DESCRIPTION:
XS GIS Cut Line= 3
      1599826.06      6871904.82      1599718.42      6872693.02
      1599510.08      6873238.16
#Sta/Elev= 30
    4209 1666.91  4322.9 1661.67    4407 1655.32  4565.5 1654.19  4585.6 1646.54
  4604.9 1646.06  4706.8 1646.21  4726.9 1650.58    4737 1649.85  4747.1 1646.21
  4772.8 1646.01  4858.1 1646.31  4880.2 1654.21  4916.3 1648.74  4921.3 1649.59
    4949 1643.13  4969.2 1643.02  4979.3 1640.99  4999.4 1643.54    5042 1642.66
  5051.7 1644.82  5057.1 1643.39  5063.4 1645.56  5141.9  1646.3  5250.2 1640.41
  5250.8 1639.91  5283.3 1640.41  5288.2 1644.64  5396.4 1662.03  5588.1 1667.52
#Mann= 7 ,-1 , 0
    4209     .05       0    4407    .075       0  4604.9     .05       0
  4772.8    .075       0  4880.2     .05       0  5250.2     .03       0
  5283.3     .05       0
Bank Sta=5250.2,5283.3
XS Rating Curve= 0 ,0
Exp/Cntr=0.3,0.1

Type RM Length L Ch R = 1 ,3386    ,459,459,459
BEGIN DESCRIPTION:
Buck Creek 3385.85
END DESCRIPTION:
XS GIS Cut Line= 3
      1599544.82      6871703.39      1599388.56      6872543.71
      1599305.22      6873002.07
#Sta/Elev= 30
  4148.7 1668.66  4204.2 1669.96  4214.4 1668.36  4224.6 1669.25  4287.6 1667.86
  4316.1 1665.97    4367 1658.78  4438.2 1651.98  4468.7 1647.24  4539.9 1643.66
  4631.4 1641.47  4743.3 1643.55  4763.7 1645.09    4784 1649.79  4814.5 1654.47
  4824.7 1654.43  4926.4 1645.81  4999.1 1643.96  5003.1 1641.24  5008.1 1641.24
  5011.5  1638.8  5012.1  1638.3  5044.7  1638.8  5047.3 1640.72  5105.8 1642.53
  5129.8 1651.85  5139.9 1654.24  5190.7 1661.55  5217.6 1662.91  5469.3 1664.52
#Mann= 3 ,-1 , 0
  4148.7     .05       0  5011.5     .03       0  5044.7     .05       0
Bank Sta=5011.5,5044.7
XS Rating Curve= 0 ,0
Exp/Cntr=0.3,0.1

Type RM Length L Ch R = 1 ,2927    ,877,877,877
BEGIN DESCRIPTION:
Buck Creek 2927.44
END DESCRIPTION:
XS GIS Cut Line= 3
      1599329.52       6871686.1      1599041.34       6872581.9
      1599072.58      6872897.84
#Sta/Elev= 30
  4067.5 1666.96  4097.2 1666.44  4166.6  1658.5  4216.6 1655.28  4248.1 1649.97
  4269.1 1647.36  4279.6 1647.04  4447.7 1644.22  4594.7 1643.38  4685.2  1644.4
  4690.4 1646.31  4710.3 1648.42  4722.5  1651.6  4741.8 1653.97  4754.6 1652.53
  4781.4 1646.78  4804.8 1644.25  4850.9 1642.89  4904.6 1643.28  4962.4    1643
  4972.9 1639.43  4976.4 1636.57  4977.3 1635.84  4977.9 1635.34  5010.5 1635.84
  5014.6 1640.69  5044.8 1654.15  5054.8 1657.25  5064.9 1658.13    5326 1661.83
#Mann= 5 ,-1 , 0
  4067.5     .05       0  4904.6     .12       0  4976.4     .05       0
  4977.3     .05       0  5010.5     .05       0
Bank Sta=4977.3,5010.5
XS Rating Curve= 0 ,0
Exp/Cntr=0.3,0.1

Type RM Length L Ch R = 1 ,2050    ,846,846,846
BEGIN DESCRIPTION:
Buck Creek 2049.91
END DESCRIPTION:
XS GIS Cut Line= 4
      1598898.97      6871345.79      1598919.81      6871960.38
      1598767.03      6872352.74      1598947.57      6872800.62
#Sta/Elev= 30
  4393.1 1667.56  4421.9 1664.05  4495.4 1661.65  4565.4 1656.19  4655.5 1657.76
  4695.5 1660.55  4805.6  1645.5  4955.6 1643.03  4965.6  1636.2    4973 1635.31
    5027 1639.18  5088.1 1639.19  5093.5 1637.35  5154.2 1640.33  5286.5 1637.06
  5319.9 1642.27  5391.2 1642.68    5461 1643.13  5510.2 1641.56  5515.2 1634.56
  5515.8 1634.06  5548.5 1634.56  5553.4 1638.47  5570.2 1635.82  5594.3 1637.32
  5599.7 1635.74  5618.1 1640.84  5637.2 1642.61  5693.5 1654.43    5912 1659.83
#Mann= 9 ,-1 , 0
  4393.1     .05       0    4973     .12       0  5154.2     .05       0
  5319.9     .12       0  5391.2     .05       0    5461     .12       0
  5515.2     .07       0  5548.5     .12       0  5637.2     .05       0
Bank Sta=5515.2,5548.5
XS Rating Curve= 0 ,0
Exp/Cntr=0.3,0.1

Type RM Length L Ch R = 1 ,1204    ,726,726,726
BEGIN DESCRIPTION:
Buck Creek 1203.96
END DESCRIPTION:
XS GIS Cut Line= 4
       1598448.8      6871313.79      1598466.16      6871740.85
      1598528.66      6872112.37      1598844.63       6872671.4
#Sta/Elev= 30
  4575.9 1665.31  4780.3 1657.79  4860.3 1657.13  4880.4 1655.74  4910.4  1652.2
  4950.4 1644.59  4960.4 1639.82  4963.7 1633.48  4964.4 1632.98  4997.1 1633.48
  4999.4 1635.59  5024.9 1639.98  5031.2 1639.47  5051.1 1642.28  5086.7 1641.31
  5380.1 1644.06  5419.3 1642.37  5446.7 1637.47    5490 1642.29  5543.5 1643.69
  5742.6 1642.89    5800 1644.61  5807.7  1643.1  5813.4 1643.71    5823 1638.56
    5851 1640.52  5866.9 1643.76  5872.6 1642.85  5937.9 1653.16  6022.2 1657.13
#Mann= 4 ,-1 , 0
  4575.9     .05       0  4963.7     .07       0  4997.1     .05       0
  5024.9     .05       0
Bank Sta=4963.7,4997.1
XS Rating Curve= 0 ,0
Exp/Cntr=0.3,0.1

Type RM Length L Ch R = 1 ,478     ,324,324,324
BEGIN DESCRIPTION:
Buck Creek 478.43
END DESCRIPTION:
XS GIS Cut Line= 3
       1597875.9      6871456.16      1598059.91       6871834.6
      1598781.08      6872656.31
#Sta/Elev= 30
    4581 1662.27  4775.5 1660.09  4888.2 1655.58  4927.8 1650.39  4933.4 1647.52
  4961.5 1638.92  4967.3 1631.85  4967.9 1631.35  5000.7 1631.85  5000.9 1633.37
    5008 1633.79  5050.2 1641.03  5062.5 1640.81  5121.3 1641.32  5156.4  1638.7
    5164 1641.46  5178.2 1642.37  5525.2 1643.92  5589.1 1643.05  5603.4  1642.3
    5610 1640.29  5702.1  1643.7  5893.7 1645.22  5914.6 1642.31  5936.4 1643.76
  5943.1 1642.34  5964.3 1645.45  5992.4 1646.23    6057 1653.14  6095.1 1655.23
#Mann= 5 ,-1 , 0
    4581     .05       0  4967.3     .05       0  5000.7     .05       0
    5008     .12       0  5062.5     .05       0
Bank Sta=4967.3,5000.7
XS Rating Curve= 0 ,0
Exp/Cntr=0.3,0.1

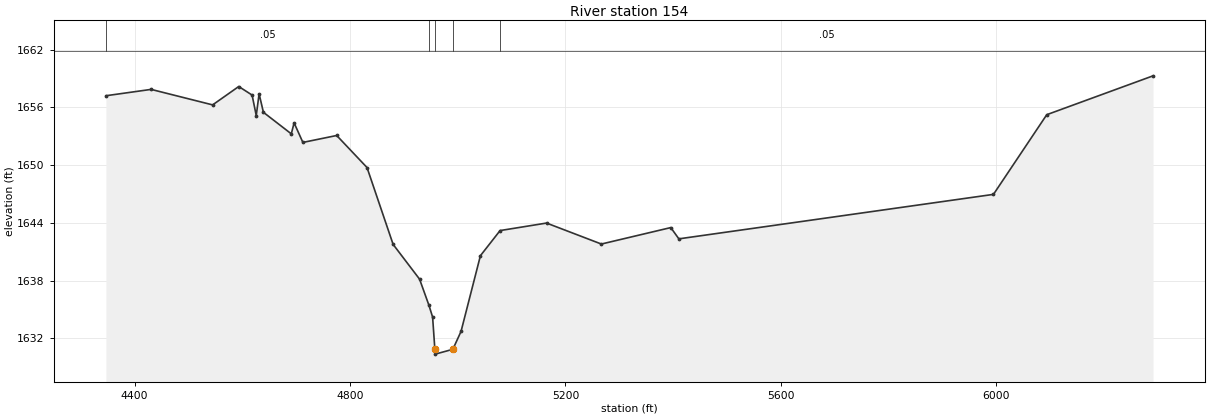
Type RM Length L Ch R = 1 ,154     ,0,0,0
BEGIN DESCRIPTION:
Buck Creek 603.242
END DESCRIPTION:
XS GIS Cut Line= 3
      1597636.29      6871438.74      1597830.44      6872062.52
      1598900.09      6872785.92
#Sta/Elev= 30
  4346.7 1657.21  4430.7 1657.87  4544.9 1656.26  4593.4 1658.17  4618.2 1657.28
  4625.9 1655.15  4631.2 1657.41  4639.2 1655.49    4691 1653.25  4696.2 1654.39
  4712.5 1652.36  4775.3 1653.08  4831.6 1649.75  4880.1 1641.76  4929.2 1638.15
  4946.7 1635.42  4953.4 1634.21  4957.6 1630.86  4958.2 1630.36    4991 1630.86
  5006.2 1632.72  5042.2 1640.59  5078.7  1643.2    5165 1643.98  5266.8  1641.8
  5395.7 1643.51  5410.7 1642.34  5994.9 1646.96  6093.9 1655.24  6291.3 1659.28
#Mann= 5 ,-1 , 0
  4346.7     .05       0  4946.7     .12       0  4957.6     .07       0
    4991     .12       0  5078.7     .05       0
Bank Sta=4957.6,4991
XS Rating Curve= 0 ,0
Exp/Cntr=0.3,0.1

Chan Stop Cuts=-1
Use User Specified Reach Order=0
Composite Channel Slope=5