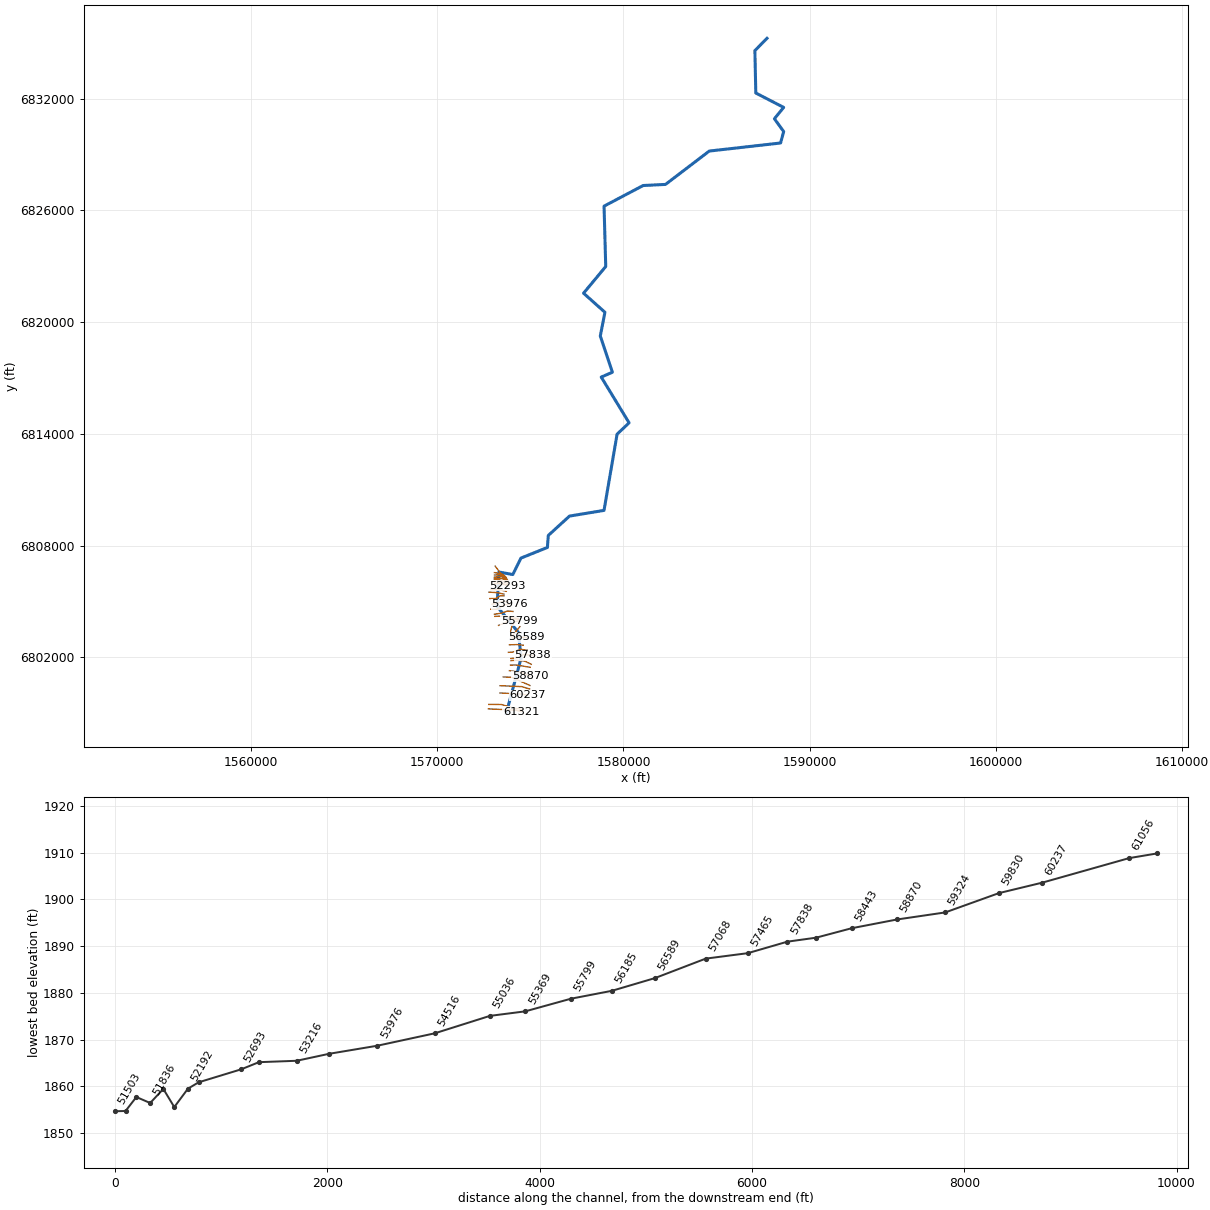
--- Buttonwillow Creek.prj (project) ---

Proj Title=Buttonwillow Creek Base Level Engineering
Current Plan=p01
Default Exp/Contr=0.3,0.1
English Units
Geom File=g01
Flow File=f01
Plan File=p01
Y Axis Title=Elevation
X Axis Title(PF)=Main Channel Distance
X Axis Title(XS)=Station
BEGIN DESCRIPTION:
Buttonwillow Creek
END DESCRIPTION:
DSS Export Rating Curves= 0
DSS Export Rating Curve Sorted= 0
DSS Export Volume Flow Curves= 0
DXF OffsetX= 0
DXF OffsetY= 0
DXF ScaleX= 1
DXF ScaleY= 10

--- Buttonwillow Creek.p01 (plan) ---

Plan Title=Multiple Run
Short Identifier=Multiple
Geom File=g01
Flow File=f01
Subcritical Flow
K Sum by GR= 0
Std Step Tol= 0.01
Critical Tol= 0.01
Num of Std Step Trials= 20
Max Error Tol= 0.3
Flow Tol Ratio= 0.001
Split Flow NTrial= 30
Split Flow Tol= 0.02
Split Flow Ratio= 0.02
Log Output Level= 0
Friction Slope Method= 1
Unsteady Friction Slope Method= 2
Unsteady Bridges Friction Slope Method= 1
Parabolic Critical Depth
Global Vel Dist=  1 , 1 , 1
Global Log Level= 0
CheckData=True
Encroach Param= -1, 0, 0, 0
BEGIN DESCRIPTION:
Multiple Run
END DESCRIPTION:

--- Buttonwillow Creek.f01 (steady flow) ---

Flow Title=Multiple
Program Version=4.10
Number of Profiles= 7
Profile Names=10-year,25-year,50-year,1pct_min,100-year,1pct_plu,500-year
River Rch & RM=Buttonwillow Cre,Reach-1         ,61321
     220     303     371     282     452     621     677
River Rch & RM=Buttonwillow Cre,Reach-1         ,55369
     319     446     552     423     677     932    1040
River Rch & RM=Buttonwillow Cre,Reach-1         ,47320
     364     512     635     488     782    1080    1200
River Rch & RM=Buttonwillow Cre,Reach-1         ,41724
     603     867    1090     849    1360    1870    2140
River Rch & RM=Buttonwillow Cre,Reach-1         ,41073
     603     867    1090     849    1360    1870    2140
River Rch & RM=Buttonwillow Cre,Reach-1         ,36136
     631     906    1140     885    1420    1950    2230
River Rch & RM=Buttonwillow Cre,Reach-1         ,28824
     697    1000    1260     983    1580    2170    2480
River Rch & RM=Buttonwillow Cre,Reach-1         ,24364
     760    1100    1380    1080    1730    2380    2730
River Rch & RM=Buttonwillow Cre,Reach-1         ,20070
     779    1120    1410    1100    1760    2430    2780
River Rch & RM=Buttonwillow Cre,Reach-1         ,15790
     853    1230    1560    1220    1950    2680    3090
River Rch & RM=Buttonwillow Cre,Reach-1         ,12464
     888    1290    1630    1270    2040    2800    3240
River Rch & RM=Buttonwillow Cre,Reach-1         ,8474
     922    1340    1690    1320    2120    2910    3370
Boundary for River Rch & Prof#=Buttonwillow Cre,Reach-1         , 1
Up Type= 0
Dn Type= 3
Dn Slope=0.001
Boundary for River Rch & Prof#=Buttonwillow Cre,Reach-1         , 2
Up Type= 0
Dn Type= 3
Dn Slope=0.001
Boundary for River Rch & Prof#=Buttonwillow Cre,Reach-1         , 3
Up Type= 0
Dn Type= 3
Dn Slope=0.001
Boundary for River Rch & Prof#=Buttonwillow Cre,Reach-1         , 4
Up Type= 0
Dn Type= 3
Dn Slope=0.001
Boundary for River Rch & Prof#=Buttonwillow Cre,Reach-1         , 5
Up Type= 0
Dn Type= 3
Dn Slope=0.001
Boundary for River Rch & Prof#=Buttonwillow Cre,Reach-1         , 6
Up Type= 0
Dn Type= 3
Dn Slope=0.001
Boundary for River Rch & Prof#=Buttonwillow Cre,Reach-1         , 7
Up Type= 0
Dn Type= 3
Dn Slope=0.001
DSS Import GetInterval= 0
DSS Import GetPeak= 0
DSS Import FillOption= 0

--- Buttonwillow Creek.g01 (geometry) ---

Geom Title=Existing Conditions
Program Version=4.10

River Reach=Buttonwillow Cre,Reach-1
Reach XY= 30
        1573705.        6798988.       1574505.3      6801967.82
      1574351.45      6803336.53       1573212.5      6804734.87
        1573308.      6806580.05      1574057.31      6806443.06
      1574494.94      6807327.39      1575915.17      6807898.28
      1575962.45      6808544.03      1577102.73      6809582.95
        1578955.        6809888.      1579656.94      6813982.29
      1580301.22      6814589.56      1578806.01      6817047.46
       1579405.3      6817306.37      1578755.19      6819252.12
      1579003.17      6820526.85      1577855.54      6821551.86
      1579046.96      6822984.68      1578956.62      6826226.17
      1581056.58      6827334.17      1582257.45      6827393.46
      1584606.46      6829184.46      1588435.53      6829617.46
      1588602.66      6830232.48      1588104.93      6830919.72
      1588601.44      6831529.85      1587105.54      6832301.86
       1587056.2      6834578.42        1587705.        6835238.

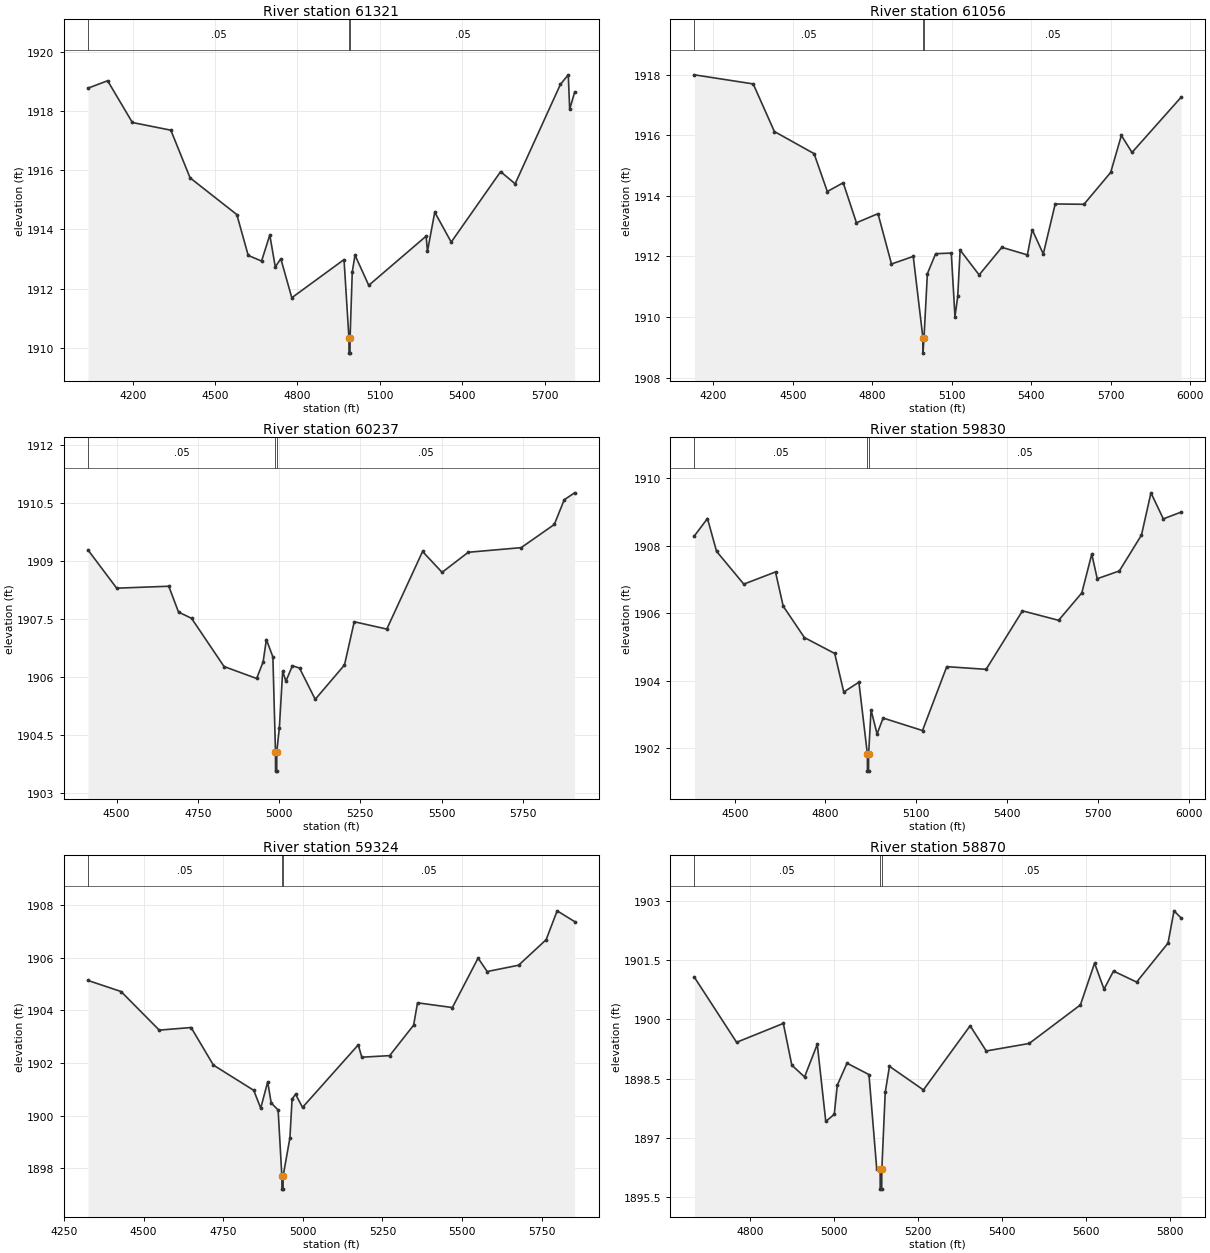
Type RM Length L Ch R = 1 ,61321   ,265,265,265
BEGIN DESCRIPTION:
Buttonwillow Creek 60704.919
END DESCRIPTION:
XS GIS Cut Line= 3
      1572743.57      6799229.57      1574210.62      6799162.29
        1574505.        6799088.
#Sta/Elev= 30
  4037.2 1918.77  4108.7 1919.02  4198.8 1917.61  4338.9 1917.35    4409 1915.74
  4579.2  1914.5  4620.7 1913.12  4669.3 1912.93  4699.3 1913.81  4719.3 1912.73
  4739.4 1913.01  4779.4 1911.69  4969.6 1912.98  4987.6 1910.32  4987.9 1909.82
  4991.4 1909.82  4991.6 1910.32  4999.6 1912.56  5009.6 1913.13  5059.7 1912.11
  5268.5 1913.77  5273.5 1913.26    5300 1914.58    5360 1913.57  5539.9 1915.95
  5592.8 1915.54  5757.8  1918.9  5786.3 1919.22  5791.4 1918.06  5809.4 1918.63
#Mann= 3 ,-1 , 0
  4037.2     .05       0  4987.6     .05       0  4991.6     .05       0
Bank Sta=4987.6,4991.6
XS Rating Curve= 0 ,0
Exp/Cntr=0.3,0.1

Type RM Length L Ch R = 1 ,61056   ,819,819,819
BEGIN DESCRIPTION:
Mapping XS 83319f5f
END DESCRIPTION:
XS GIS Cut Line= 4
       1572763.1      6799470.45       1573448.9      6799463.94
      1574125.99      6799264.29      1574568.68      6799205.69
#Sta/Elev= 30
  4128.1 1917.99    4350 1917.69    4430 1916.12    4580 1915.39    4630 1914.14
    4690 1914.43    4740 1913.11  4821.4 1913.41  4872.4 1911.75  4954.6    1912
  4991.2 1909.31  4991.4 1908.81  4995.2 1909.31    5008 1911.43  5039.2 1912.09
  5098.3 1912.11  5112.2 1910.01  5122.6 1910.68  5131.7 1912.21  5203.5 1911.39
  5289.4  1912.3  5385.7 1912.05  5404.1 1912.88  5445.8 1912.08  5490.9 1913.73
  5599.5 1913.72  5700.4 1914.77  5740.8 1915.99  5781.1 1915.43  5966.4 1917.25
#Mann= 3 ,-1 , 0
  4128.1     .05       0  4991.2     .05       0  4995.2     .05       0
Bank Sta=4991.2,4995.2
XS Rating Curve= 0 ,0
Exp/Cntr=0.3,0.1

Type RM Length L Ch R = 1 ,60237   ,407,407,407
BEGIN DESCRIPTION:
Mapping XS 84750597
END DESCRIPTION:
XS GIS Cut Line= 3
      1573366.82      6800083.73      1574517.91      6800029.04
      1574856.42      6799963.95
#Sta/Elev= 30
  4412.2 1909.29  4500.5  1908.3  4660.7 1908.35  4690.7 1907.68  4730.7 1907.52
  4830.8 1906.27    4931 1905.96    4951 1906.39    4961 1906.97    4981 1906.52
    4989 1904.06  4989.3 1903.56  4992.8 1903.56    4993 1904.06    5001 1904.69
  5011.1 1906.15  5021.1 1905.89  5041.1 1906.29    5063 1906.23  5111.2 1905.42
  5201.3 1906.31  5231.3 1907.43  5331.4 1907.24  5441.5 1909.25  5501.6 1908.71
    5582 1909.23  5744.9 1909.35  5846.8 1909.95  5877.3 1910.59  5909.3 1910.77
#Mann= 3 ,-1 , 0
  4412.2     .05       0    4989     .05       0    4993     .05       0
Bank Sta=4989,4993
XS Rating Curve= 0 ,0
Exp/Cntr=0.3,0.1

Type RM Length L Ch R = 1 ,59830   ,506,506,506
BEGIN DESCRIPTION:
Mapping XS e8e6fd89
END DESCRIPTION:
XS GIS Cut Line= 3
      1573372.05      6800474.36      1574536.14      6800424.88
      1574960.35      6800297.36
#Sta/Elev= 30
    4367 1908.29    4410  1908.8    4440 1907.83  4530.1 1906.86  4634.8 1907.22
  4660.2 1906.21  4730.3 1905.28  4830.4 1904.81  4860.4 1903.67  4910.4 1903.96
  4938.5 1901.83  4938.7 1901.33  4942.2 1901.33  4942.5 1901.83  4950.5 1903.14
  4970.5 1902.43  4990.5  1902.9  5120.6 1902.53  5200.7 1904.42  5330.8 1904.34
  5450.9 1906.07  5570.4 1905.79    5647  1906.6    5680 1907.75    5698 1907.02
  5771.1 1907.25  5844.2 1908.31  5875.5 1909.56  5916.4 1908.79  5975.1 1908.99
#Mann= 3 ,-1 , 0
    4367     .05       0  4938.5     .05       0  4942.5     .05       0
Bank Sta=4938.5,4942.5
XS Rating Curve= 0 ,0
Exp/Cntr=0.3,0.1

Type RM Length L Ch R = 1 ,59324   ,454,454,454
BEGIN DESCRIPTION:
Mapping XS f9769047
END DESCRIPTION:
XS GIS Cut Line= 4
      1573541.34      6800943.11      1573984.06      6800930.09
      1574898.12      6800523.84      1574973.63      6800484.78
#Sta/Elev= 30
  4325.5 1905.14  4429.2 1904.72  4549.3 1903.25  4649.3 1903.35  4719.3 1901.92
    4846 1900.96  4867.9 1900.28  4889.8 1901.28  4900.8 1900.48  4922.6 1900.21
  4934.3  1897.7  4934.6  1897.2  4938.1  1897.2  4938.3  1897.7  4959.6 1899.15
  4966.4 1900.63  4977.4 1900.81  4999.2 1900.31  5174.3 1902.69  5185.3 1902.22
  5272.8 1902.28  5348.1 1903.44  5360.4 1904.29  5469.8 1904.11  5550.5 1905.99
  5579.2 1905.48  5677.7 1905.72  5764.2 1906.69  5798.9 1907.79  5853.7 1907.38
#Mann= 3 ,-1 , 0
  4325.5     .05       0  4934.3     .05       0  4938.3     .05       0
Bank Sta=4934.3,4938.3
XS Rating Curve= 0 ,0
Exp/Cntr=0.3,0.1

Type RM Length L Ch R = 1 ,58870   ,427,427,427
BEGIN DESCRIPTION:
Mapping XS 4476310a
END DESCRIPTION:
XS GIS Cut Line= 3
      1573875.69      6801281.97       1574565.8      6801182.15
      1574980.11      6800980.42
#Sta/Elev= 30
  4667.5 1901.07  4767.8 1899.42    4879  1899.9  4899.2 1898.84  4929.5 1898.54
  4959.8 1899.37    4980 1897.41  5000.2 1897.59  5007.4 1898.33  5030.5 1898.89
  5082.8  1898.6  5101.3  1896.2  5109.4 1896.19  5109.6 1895.69  5113.1 1895.69
  5113.4 1896.19  5121.5 1898.15  5131.6 1898.81  5212.4 1898.21  5323.6 1899.84
  5361.9  1899.2    5464 1899.39    5586 1900.37  5619.7 1901.43  5642.2 1900.77
  5664.8 1901.23  5719.8 1900.95  5794.5 1901.94  5808.8 1902.76  5825.6 1902.58
#Mann= 3 ,-1 , 0
  4667.5     .05       0  5109.4     .05       0  5113.4     .05       0
Bank Sta=5109.4,5113.4
XS Rating Curve= 0 ,0
Exp/Cntr=0.3,0.1

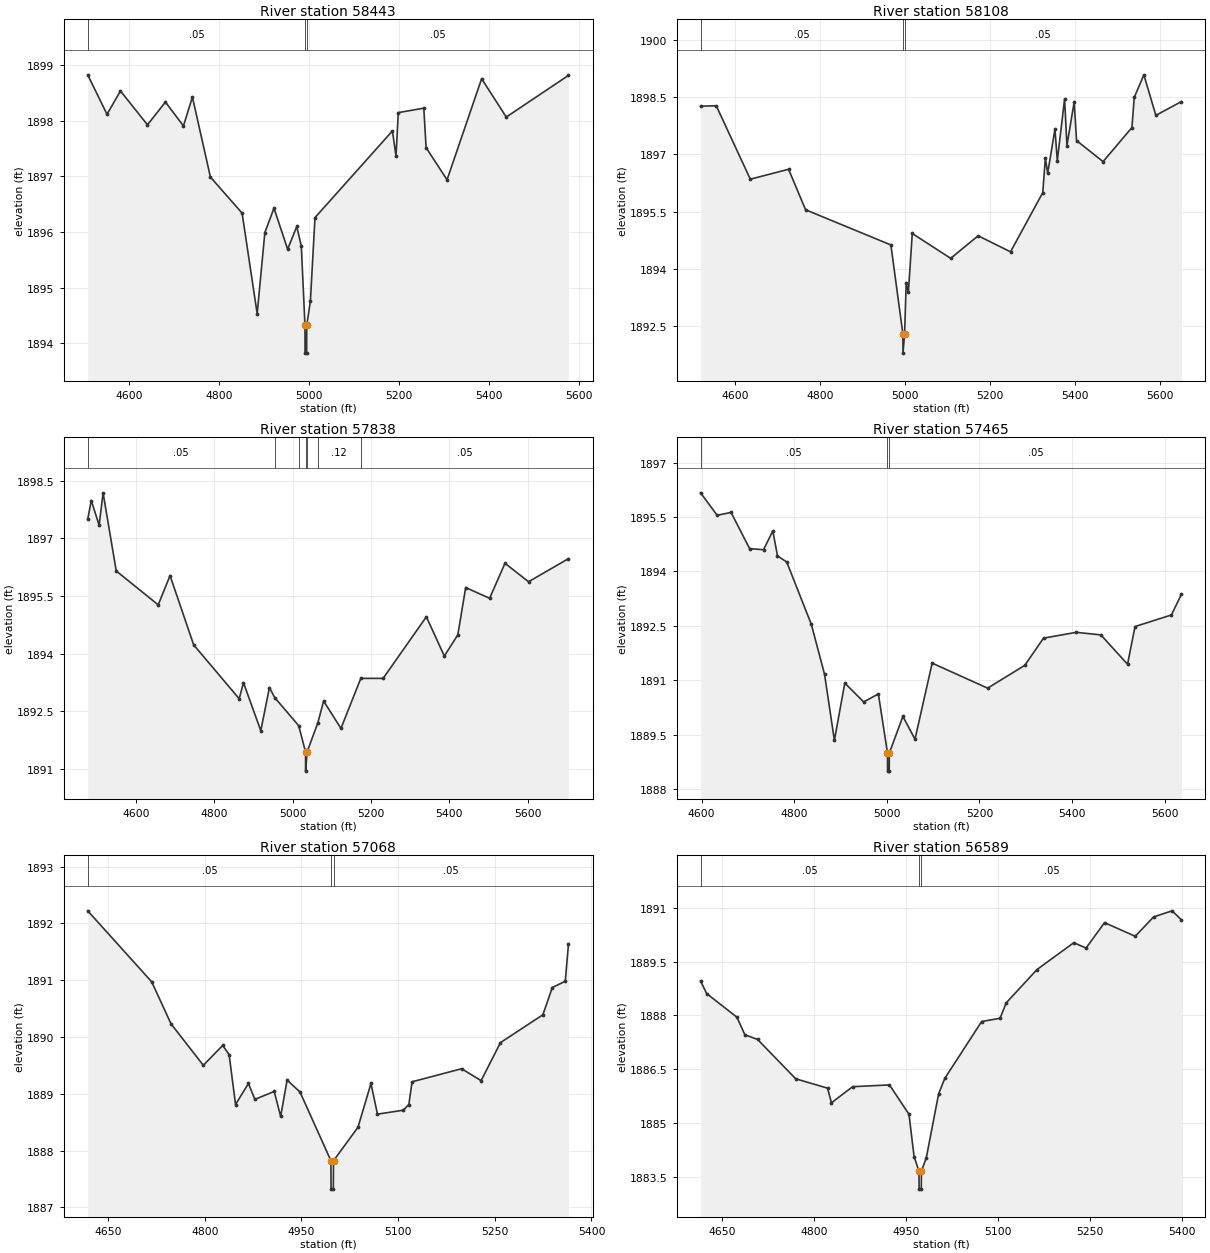
Type RM Length L Ch R = 1 ,58443   ,335,335,335
BEGIN DESCRIPTION:
Mapping XS 26a9deb3
END DESCRIPTION:
XS GIS Cut Line= 3
      1573932.07      6801581.45      1574240.28      6801583.62
      1574991.64      6801462.37
#Sta/Elev= 30
  4508.2 1898.83  4551.1 1898.12  4581.1 1898.54  4641.1 1897.93  4681.1 1898.34
  4721.1 1897.91  4741.1 1898.43  4781.1 1896.99  4851.6 1896.34  4885.1 1894.53
  4902.2 1895.99  4922.5 1896.43  4952.9 1895.69  4973.1  1896.1  4983.3 1895.75
  4991.4 1894.32  4991.6 1893.82  4995.1 1893.82  4995.4 1894.32  5003.5 1894.76
  5013.7 1896.26  5185.9 1897.82  5193.9 1897.37    5199 1898.15  5255.7 1898.23
  5260.8 1897.52  5307.4 1896.94  5384.3 1898.76  5439.1 1898.07  5577.5 1898.82
#Mann= 3 ,-1 , 0
  4508.2     .05       0  4991.4     .05       0  4995.4     .05       0
Bank Sta=4991.4,4995.4
XS Rating Curve= 0 ,0
Exp/Cntr=0.3,0.1

Type RM Length L Ch R = 1 ,58108   ,270,270,270
BEGIN DESCRIPTION:
Mapping XS a8d04f42
END DESCRIPTION:
XS GIS Cut Line= 4
      1573958.12      6801822.34      1574266.32      6801844.04
      1574700.35      6801791.96      1575049.74      6801624.86
#Sta/Elev= 30
  4518.1 1898.26  4555.1 1898.27  4635.3 1896.35  4725.5 1896.61  4765.6 1895.55
  4966.7 1894.63    4995  1892.3  4995.2  1891.8    4999  1892.3  5002.8 1893.64
  5007.9 1893.39  5017.1 1894.93  5107.7 1894.28  5172.4 1894.87  5248.7 1894.45
  5324.8    1896  5330.8  1896.9  5336.4 1896.51  5353.5 1897.66    5359 1896.83
  5376.2 1898.45  5381.7 1897.23  5398.8 1898.37  5404.4 1897.36  5466.9 1896.81
  5534.9  1897.7  5540.4 1898.49  5563.1 1899.08  5591.3 1898.02  5651.5 1898.38
#Mann= 3 ,-1 , 0
  4518.1     .05       0    4995     .05       0    4999     .05       0
Bank Sta=4995,4999
XS Rating Curve= 0 ,0
Exp/Cntr=0.3,0.1

Type RM Length L Ch R = 1 ,57838   ,373,373,373
BEGIN DESCRIPTION:
Mapping XS a5bbf399
END DESCRIPTION:
XS GIS Cut Line= 4
      1573955.96      6801935.18      1574290.19      6801972.08
      1574633.07      6802150.03      1575136.54      6802104.46
#Sta/Elev= 30
  4476.6 1897.49  4485.7 1897.98  4505.8 1897.34  4515.9 1898.18  4549.5 1896.15
  4656.7 1895.27  4686.9 1896.03  4747.3 1894.23  4863.6 1892.83  4874.5 1893.25
  4918.7    1892  4940.8 1893.12  4954.4 1892.86  5015.6 1892.13    5033 1891.45
  5033.2 1890.95    5037 1891.45  5064.3  1892.2  5079.2 1892.77  5123.5 1892.06
  5174.2 1893.36  5231.2 1893.36  5341.7 1894.96  5387.5 1893.94    5422 1894.49
  5442.1 1895.72  5503.2 1895.44  5542.5 1896.35  5602.7 1895.87  5704.7 1896.47
#Mann= 7 ,-1 , 0
  4476.6     .05       0  4954.4     .12       0  5015.6     .05       0
    5033     .07       0    5037     .05       0  5064.3     .12       0
  5174.2     .05       0
Bank Sta=5033,5037
XS Rating Curve= 0 ,0
Exp/Cntr=0.3,0.1

Type RM Length L Ch R = 1 ,57465   ,397,397,397
BEGIN DESCRIPTION:
Mapping XS 2c83a1ad
END DESCRIPTION:
XS GIS Cut Line= 4
      1573819.29      6802265.05      1574055.82      6802280.24
      1574483.33      6802425.64      1574830.28       6802380.1
#Sta/Elev= 30
  4597.7 1896.17  4633.5 1895.55  4663.5 1895.63  4703.6 1894.63  4733.7  1894.6
  4753.7 1895.12  4763.8 1894.43  4783.8 1894.26  4836.9 1892.54  4865.5 1891.16
  4886.7 1889.34  4909.2 1890.92    4950  1890.4  4981.7 1890.62  5001.4 1888.99
  5001.6 1888.49  5005.1 1888.49  5005.4 1888.99  5034.7    1890  5060.8 1889.37
  5097.9 1891.47  5217.7 1890.78    5298 1891.41  5338.4 1892.16    5409 1892.32
  5462.3 1892.25  5519.9 1891.44  5536.1 1892.48  5614.8  1892.8  5636.2 1893.37
#Mann= 3 ,-1 , 0
  4597.7     .05       0  5001.4     .03       0  5005.4     .05       0
Bank Sta=5001.4,5005.4
XS Rating Curve= 0 ,0
Exp/Cntr=0.3,0.1

Type RM Length L Ch R = 1 ,57068   ,479,479,479
BEGIN DESCRIPTION:
Mapping XS fd4f12ac
END DESCRIPTION:
XS GIS Cut Line= 3
      1573875.69      6802673.03      1574288.02      6802681.71
        1574620.      6802649.17
#Sta/Elev= 30
  4618.3 1892.22  4717.6 1890.97  4747.6 1890.23  4797.7  1889.5  4827.7 1889.85
  4837.7 1889.69  4847.7 1888.81  4867.7 1889.18  4877.7  1888.9  4907.7 1889.04
  4917.7  1888.6  4927.7 1889.24  4947.7 1889.03  4995.7 1887.82  4995.9 1887.32
  4999.4 1887.32  4999.7 1887.82  5037.7 1888.41  5057.8 1889.18  5067.9 1888.64
  5108.1 1888.71  5116.6 1888.81  5121.6 1889.21  5198.5 1889.44  5228.7 1889.23
  5258.8  1889.9  5324.6 1890.39  5339.2 1890.87  5359.3 1890.98  5364.3 1891.64
#Mann= 3 ,-1 , 0
  4618.3     .05       0  4995.7     .05       0  4999.7     .05       0
Bank Sta=4995.7,4999.7
XS Rating Curve= 0 ,0
Exp/Cntr=0.3,0.1

Type RM Length L Ch R = 1 ,56589   ,404,404,404
BEGIN DESCRIPTION:
Mapping XS 8625d53c
END DESCRIPTION:
XS GIS Cut Line= 3
      1574025.44      6803026.77      1574248.96      6803087.53
      1574800.11      6803063.66
#Sta/Elev= 30
  4615.6 1888.96  4625.5 1888.61  4674.8 1887.95  4687.7 1887.46  4708.4 1887.33
  4770.6 1886.23  4822.4 1885.97  4828.8 1885.56  4863.3 1886.01  4923.3 1886.06
  4955.1 1885.24  4963.4 1884.06  4971.4 1883.65  4971.6 1883.15  4975.1 1883.15
  4975.4 1883.65  4983.4 1884.03  5003.4 1885.81  5013.4 1886.24  5073.5 1887.83
  5103.5 1887.92  5113.5 1888.35  5163.6 1889.28  5223.6 1890.03  5243.6 1889.88
  5273.7 1890.59  5323.7 1890.21  5353.7 1890.75  5383.8 1890.92  5398.9 1890.67
#Mann= 3 ,-1 , 0
  4615.6     .05       0  4971.4     .03       0  4975.4     .05       0
Bank Sta=4971.4,4975.4
XS Rating Curve= 0 ,0
Exp/Cntr=0.3,0.1

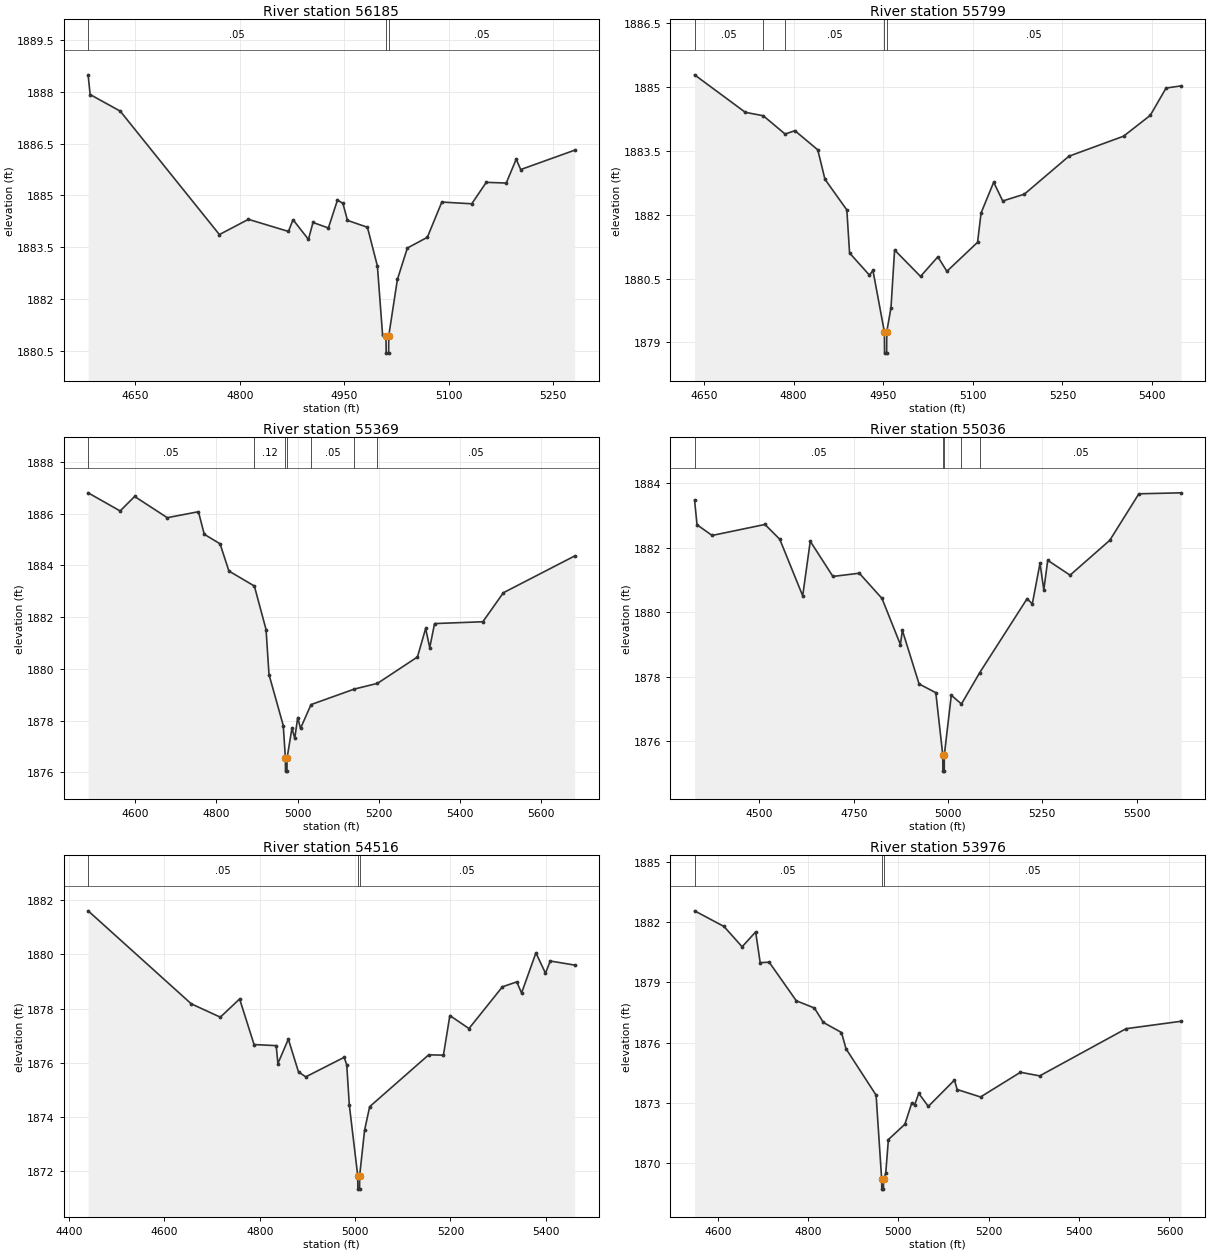
Type RM Length L Ch R = 1 ,56185   ,386,386,386
BEGIN DESCRIPTION:
Mapping XS 936f175d
END DESCRIPTION:
XS GIS Cut Line= 3
      1573999.42      6803109.26        1574173.      6803326.24
      1574441.07      6803650.52
#Sta/Elev= 30
  4582.2 1888.49  4585.1 1887.92  4628.3 1887.44  4770.7 1883.87  4812.4 1884.31
  4869.9 1883.96  4876.4  1884.3  4898.6 1883.73  4905.1 1884.22  4927.2 1884.06
  4940.3 1884.87  4948.1 1884.77  4954.6 1884.28  4983.3 1884.08  4997.6 1882.96
  5005.1 1880.95  5009.9 1880.94  5010.2 1880.44  5013.7 1880.44  5013.9 1880.94
  5026.3 1882.57  5040.6 1883.48  5069.3 1883.79  5090.1 1884.81  5133.1 1884.76
  5153.9 1885.38  5182.6 1885.36  5196.9 1886.05  5203.4 1885.75  5280.8 1886.31
#Mann= 3 ,-1 , 0
  4582.2     .05       0  5009.9     .05       0  5013.9     .05       0
Bank Sta=5009.9,5013.9
XS Rating Curve= 0 ,0
Exp/Cntr=0.3,0.1

Type RM Length L Ch R = 1 ,55799   ,430,430,430
BEGIN DESCRIPTION:
Mapping XS 2addc4f6
END DESCRIPTION:
XS GIS Cut Line= 4
      1573944.42       6803405.1      1574001.71      6803662.04
      1574170.11      6803918.98      1574409.65      6803962.38
#Sta/Elev= 30
  4634.5 1885.28  4719.4  1884.4  4749.4 1884.32    4786 1883.89  4802.3 1883.97
  4840.6 1883.52  4852.6 1882.83  4889.2 1882.11  4893.8  1881.1    4927 1880.58
  4932.9 1880.69    4952 1879.25  4952.3 1878.75  4955.8 1878.75    4956 1879.25
  4963.1 1879.82  4969.1 1881.17  5012.5 1880.55  5041.5 1881.01  5056.6 1880.67
  5107.9 1881.35  5113.8 1882.04  5134.9 1882.76    5150 1882.32  5186.2 1882.48
  5260.7 1883.37  5352.2 1883.84  5396.9 1884.33  5423.3 1884.97  5448.4 1885.02
#Mann= 5 ,-1 , 0
  4634.5     .05       0  4749.4     .12       0    4786     .05       0
    4952     .03       0    4956     .05       0
Bank Sta=4952,4956
XS Rating Curve= 0 ,0
Exp/Cntr=0.3,0.1

Type RM Length L Ch R = 1 ,55369   ,333,333,333
BEGIN DESCRIPTION:
Mapping XS 48e005d7
END DESCRIPTION:
XS GIS Cut Line= 4
      1573289.87      6803714.11       1573664.9      6803853.01
      1573888.86      6804089.12      1574359.39      6804028.35
#Sta/Elev= 30
  4483.6  1886.8  4562.6  1886.1  4598.3 1886.66  4678.8 1885.84  4755.7 1886.07
    4770  1885.2    4809 1884.83  4830.8 1883.78  4893.6  1883.2  4922.4 1881.52
  4929.7 1879.78  4964.9 1877.81  4970.1 1876.55  4970.4 1876.05    4974 1876.05
  4974.2 1876.55  4986.3 1877.71  4993.2 1877.32  5000.5 1878.12  5007.4  1877.7
  5033.3 1878.62  5140.2 1879.22  5197.2 1879.44  5295.8 1880.46    5316 1881.56
  5326.1 1880.82    5338 1881.75  5457.1 1881.82  5507.6 1882.94  5683.4 1884.36
#Mann= 7 ,-1 , 0
  4483.6     .05       0  4893.6     .12       0  4970.1     .07       0
  4974.2     .12       0  5033.3     .05       0  5140.2     .12       0
  5197.2     .05       0
Bank Sta=4970.1,4974.2
XS Rating Curve= 0 ,0
Exp/Cntr=0.3,0.1

Type RM Length L Ch R = 1 ,55036   ,520,520,520
BEGIN DESCRIPTION:
Mapping XS aef98785
END DESCRIPTION:
XS GIS Cut Line= 4
      1573088.47      6804196.76      1573600.67      6804210.65
      1574038.17       6804116.9      1574366.29      6804083.91
#Sta/Elev= 30
  4328.2 1883.47  4334.7 1882.71  4374.7 1882.38  4514.8 1882.72  4554.1 1882.26
  4614.8 1880.51  4634.8  1882.2  4694.9 1881.11  4764.9 1881.21  4824.9 1880.43
  4873.8    1879    4879 1879.44  4923.3 1877.78  4967.6 1877.51  4986.1 1875.58
  4986.4 1875.08    4990 1875.08  4990.2 1875.58  5008.7 1877.43  5035.6 1877.16
    5084 1878.13  5209.6 1880.42  5223.4 1880.26  5243.9 1881.52  5253.9 1880.69
  5264.3 1881.61  5323.5 1881.15  5428.8 1882.23  5505.9 1883.67  5617.8  1883.7
#Mann= 5 ,-1 , 0
  4328.2     .05       0  4986.1     .05       0  4990.2     .05       0
  5035.6     .12       0    5084     .05       0
Bank Sta=4986.1,4990.2
XS Rating Curve= 0 ,0
Exp/Cntr=0.3,0.1

Type RM Length L Ch R = 1 ,54516   ,540,540,540
BEGIN DESCRIPTION:
Mapping XS 164ac1df
END DESCRIPTION:
XS GIS Cut Line= 4
      1573071.12      6804311.34      1573466.99      6804373.84
      1573767.33      6804484.95      1574065.98      6804462.38
#Sta/Elev= 30
  4439.9 1881.61  4656.4 1878.18  4717.2 1877.69  4757.7 1878.36    4788 1876.68
  4834.4 1876.64    4838 1875.98  4859.9 1876.88  4881.2 1875.67  4896.5 1875.49
  4977.1 1876.21  4982.4 1875.93  4987.8 1874.45  5005.4 1871.85  5005.7 1871.35
  5009.3 1871.35  5009.5 1871.85  5019.8 1873.52  5030.5 1874.39  5154.2  1876.3
  5185.2 1876.29  5198.7 1877.75  5238.8 1877.27    5309 1878.81  5339.1 1878.99
  5349.1 1878.58  5379.2 1880.06  5399.3 1879.31  5409.3 1879.76  5460.4 1879.61
#Mann= 3 ,-1 , 0
  4439.9     .05       0  5005.4     .05       0  5009.5     .05       0
Bank Sta=5005.4,5009.5
XS Rating Curve= 0 ,0
Exp/Cntr=0.3,0.1

Type RM Length L Ch R = 1 ,53976   ,455,455,455
BEGIN DESCRIPTION:
Mapping XS a68fb2f2
END DESCRIPTION:
XS GIS Cut Line= 4
      1572869.79      6804580.44      1573213.51      6804580.44
       1573602.4       6804823.5      1573876.72      6804835.65
#Sta/Elev= 30
  4548.8 1882.56    4614 1881.78    4654 1880.77    4684 1881.51    4694 1879.98
    4714    1880    4774 1878.08    4814 1877.72    4834    1877    4874  1876.5
    4884 1875.69  4950.6 1873.38  4962.9  1869.2  4963.2  1868.7  4966.8  1868.7
  4967.1  1869.2  4971.9 1869.49  4977.8 1871.17  5014.3 1871.93  5029.7    1873
  5035.8 1872.89    5045 1873.47  5066.2 1872.82    5124 1874.13  5130.1 1873.66
  5181.8 1873.29  5270.2 1874.52  5312.7 1874.34  5503.9 1876.69  5625.7 1877.06
#Mann= 3 ,-1 , 0
  4548.8     .05       0  4962.9     .03       0  4967.1     .05       0
Bank Sta=4962.9,4967.1
XS Rating Curve= 0 ,0
Exp/Cntr=0.3,0.1

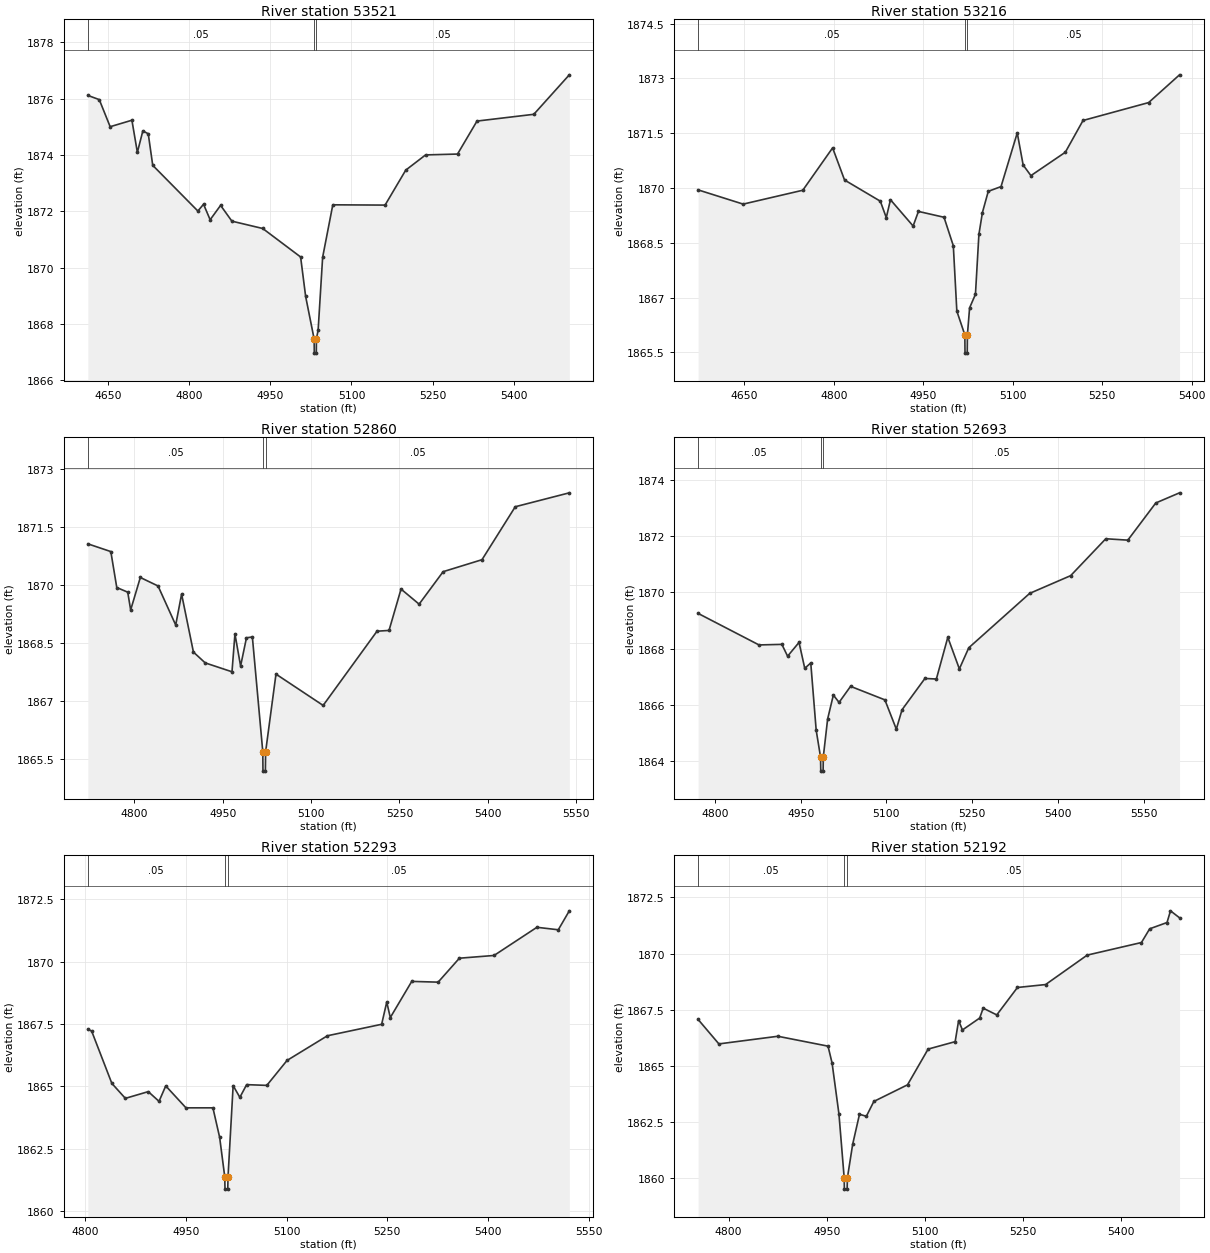
Type RM Length L Ch R = 1 ,53521   ,305,305,305
BEGIN DESCRIPTION:
Mapping XS 986013da
END DESCRIPTION:
XS GIS Cut Line= 4
      1572934.05      6804849.54      1573107.61      6804868.63
      1573538.17      6805004.05      1573800.17      6804973.02
#Sta/Elev= 30
  4612.8 1876.11  4633.9 1875.96    4654    1875  4694.2 1875.23  4704.3 1874.09
  4714.4 1874.85  4724.4 1874.75  4732.7 1873.63  4816.1 1872.01  4826.6 1872.25
  4838.8  1871.7  4858.1 1872.21    4879 1871.65    4936 1871.39    5006 1870.38
  5015.3 1868.98    5031 1867.47  5031.3 1866.97    5035 1866.97  5035.2 1867.47
  5038.4 1867.79  5046.7 1870.37  5065.5 1872.23  5162.1 1872.22  5200.3 1873.46
    5237    1874    5296 1874.03    5332  1875.2    5437 1875.44  5502.6 1876.84
#Mann= 3 ,-1 , 0
  4612.8     .05       0    5031     .05       0  5035.2     .05       0
Bank Sta=5031,5035.2
XS Rating Curve= 0 ,0
Exp/Cntr=0.3,0.1

Type RM Length L Ch R = 1 ,53216   ,356,356,356
BEGIN DESCRIPTION:
Mapping XS 5b0c948b
END DESCRIPTION:
XS GIS Cut Line= 4
      1572819.44      6805153.36      1573144.07      6805158.57
       1573390.6       6805304.4      1573586.76      6805300.93
#Sta/Elev= 30
  4572.4 1869.95    4648 1869.56    4748 1869.94    4798  1871.1    4818 1870.22
    4878 1869.64    4888 1869.19    4895 1869.68    4933 1868.96  4941.9 1869.36
  4984.8  1869.2  5000.4 1868.42  5006.3 1866.63  5019.7 1865.98    5020 1865.48
  5023.7 1865.48    5024 1865.98  5027.7 1866.72  5037.5 1867.09  5043.3 1868.73
  5049.2 1869.33    5059 1869.91  5080.4 1870.04  5107.6 1871.51  5117.5 1870.63
  5130.5 1870.34  5188.2 1870.98  5217.9 1871.85  5327.9 1872.34  5379.7  1873.1
#Mann= 3 ,-1 , 0
  4572.4     .05       0  5019.7     .03       0    5024     .05       0
Bank Sta=5019.7,5024
XS Rating Curve= 0 ,0
Exp/Cntr=0.3,0.1

Type RM Length L Ch R = 1 ,52860   ,167,167,167
BEGIN DESCRIPTION:
Mapping XS 583155de
END DESCRIPTION:
XS GIS Cut Line= 3
      1572776.02      6805497.11      1573197.89       6805472.8
      1573584.88      6805392.97
#Sta/Elev= 30
  4720.8 1871.06  4759.8 1870.86  4769.9 1869.93  4788.5 1869.81  4793.5 1869.35
  4809.9 1870.19    4840 1869.97    4870 1868.96    4880 1869.76  4900.1 1868.26
  4920.1 1867.98  4965.6 1867.75  4970.6 1868.73  4980.2  1867.9  4990.2 1868.63
  5000.2 1868.65  5017.9 1865.68  5018.2 1865.18  5022.3 1865.18  5022.7 1865.68
  5040.3 1867.69  5120.4 1866.88  5211.9  1868.8  5232.3 1868.82  5252.7 1869.89
  5283.4  1869.5  5324.2 1870.34  5390.2 1870.65  5446.7 1872.02  5538.5 1872.38
#Mann= 3 ,-1 , 0
  4720.8     .05       0  5017.9     .05       0  5022.7     .05       0
Bank Sta=5017.9,5022.7
XS Rating Curve= 0 ,0
Exp/Cntr=0.3,0.1

Type RM Length L Ch R = 1 ,52693   ,400,400,400
BEGIN DESCRIPTION:
Mapping XS 6d769a8d
END DESCRIPTION:
XS GIS Cut Line= 3
      1572878.48        6805636.      1573324.63      6805629.05
      1573710.91      6805544.17
#Sta/Elev= 30
  4770.7 1869.25  4877.2 1868.13  4917.2 1868.15  4927.2 1867.73  4947.2 1868.22
  4957.2  1867.3  4967.7 1867.49  4977.2  1865.1  4984.8 1864.15  4985.2 1863.65
  4989.3 1863.65  4989.6 1864.15  4997.2  1865.5  5007.2 1866.35  5017.2 1866.09
  5037.3 1866.66  5097.3 1866.18  5117.3 1865.14  5127.3 1865.83  5167.3 1866.94
  5187.3 1866.92  5207.3  1868.4  5227.5 1867.28    5244 1868.03  5350.4 1869.96
  5422.1 1870.59  5483.5  1871.9    5522 1871.85  5570.9 1873.17  5612.4 1873.53
#Mann= 3 ,-1 , 0
  4770.7     .05       0  4984.8     .03       0  4989.6     .05       0
Bank Sta=4984.8,4989.6
XS Rating Curve= 0 ,0
Exp/Cntr=0.3,0.1

Type RM Length L Ch R = 1 ,52293   ,101,101,101
BEGIN DESCRIPTION:
Mapping XS c300449c
END DESCRIPTION:
XS GIS Cut Line= 3
      1573059.37      6805969.24      1573485.13      6805939.29
      1573760.59      6805849.64
#Sta/Elev= 30
  4804.3 1867.29  4809.9 1867.22    4840 1865.12  4860.1 1864.52  4894.2 1864.79
  4910.2  1864.4  4920.2 1865.02  4950.3 1864.14  4990.4 1864.14  5000.4 1862.96
    5008 1861.38  5008.4 1860.88  5012.5 1860.88  5012.9 1861.38  5020.5 1865.03
  5030.5 1864.56  5040.6 1865.07  5070.6 1865.04  5100.7 1866.04  5160.8 1867.03
  5241.5 1867.49  5249.1 1868.38  5254.4 1867.76  5286.3 1869.21  5325.6 1869.18
  5357.2 1870.14  5408.8 1870.25  5472.6 1871.38  5504.4 1871.28  5520.8 1872.04
#Mann= 3 ,-1 , 0
  4804.3     .05       0    5008     .05       0  5012.9     .05       0
Bank Sta=5008,5012.9
XS Rating Curve= 0 ,0
Exp/Cntr=0.3,0.1

Type RM Length L Ch R = 1 ,52192   ,129,129,129
BEGIN DESCRIPTION:
Mapping XS d9e18e37
END DESCRIPTION:
XS GIS Cut Line= 4
      1573063.19      6806074.29      1573204.25      6806069.95
      1573473.35      6805985.31      1573770.32      6805887.77
#Sta/Elev= 30
  4753.3 1867.07  4785.1 1865.98  4875.2 1866.32  4951.9 1865.88  4958.1 1865.13
  4968.6 1862.86  4976.6 1860.02  4976.9 1859.52  4981.1 1859.52  4981.5 1860.02
  4989.6 1861.52    5000 1862.85  5010.5 1862.76  5021.9 1863.42  5073.4 1864.16
  5104.9 1865.75  5146.2 1866.08  5151.5 1867.02  5157.3  1866.6  5183.7 1867.13
    5189 1867.57  5209.8 1867.27  5241.4 1868.49  5284.4 1868.62    5348 1869.93
  5430.9 1870.49  5443.5  1871.1    5470 1871.38  5475.3  1871.9  5489.1 1871.59
#Mann= 3 ,-1 , 0
  4753.3     .05       0  4976.6     .05       0  4981.5     .05       0
Bank Sta=4976.6,4981.5
XS Rating Curve= 0 ,0
Exp/Cntr=0.3,0.1

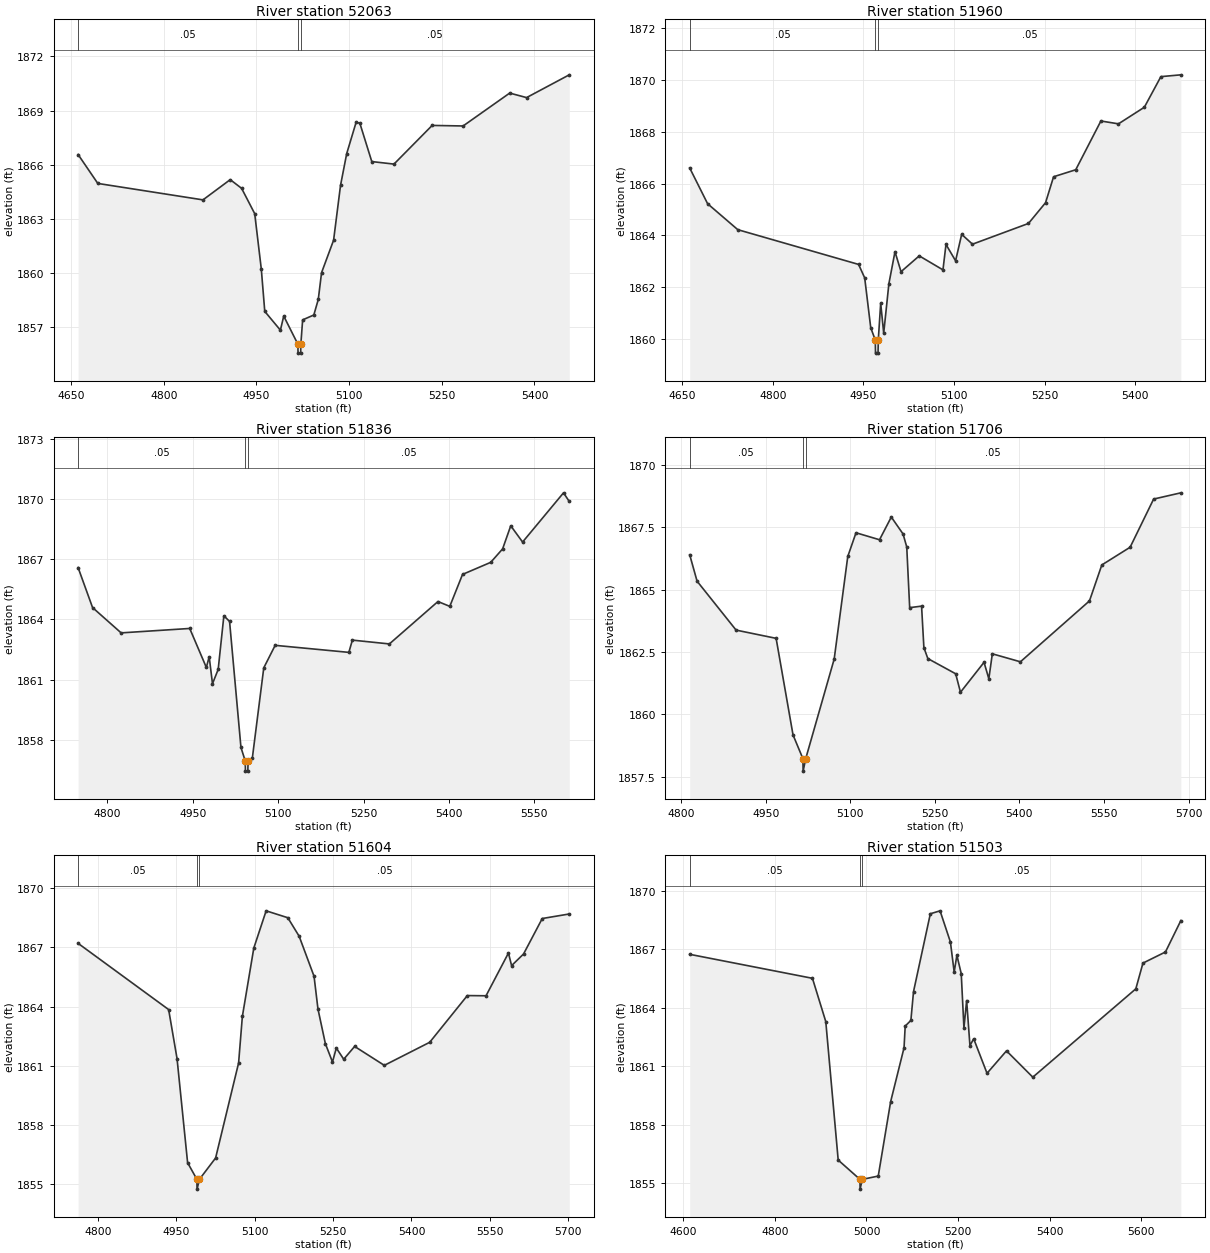
Type RM Length L Ch R = 1 ,52063   ,103,103,103
BEGIN DESCRIPTION:
Mapping XS 37429375
END DESCRIPTION:
XS GIS Cut Line= 4
      1573063.14      6806180.63      1573286.72      6806169.78
      1573712.07       6806015.7      1573788.04      6805924.53
#Sta/Elev= 30
  4661.4 1866.57  4693.3 1864.97  4863.5 1864.06  4907.6 1865.18    4926  1864.7
  4947.2  1863.3  4957.9 1860.23  4963.5 1857.89  4988.8 1856.85  4994.2 1857.63
    5017 1856.08  5017.4 1855.58  5021.6 1855.58  5021.9 1856.08  5024.8 1857.42
  5042.9 1857.69  5050.1 1858.55  5055.4 1860.03  5074.9 1861.83  5086.1 1864.86
  5096.1 1866.62  5111.4 1868.36  5117.4  1868.3  5136.7 1866.18  5172.6 1866.04
  5234.4 1868.18  5284.5 1868.15  5359.9 1869.97  5387.2 1869.72  5456.3 1870.98
#Mann= 3 ,-1 , 0
  4661.4     .05       0    5017     .05       0  5021.9     .05       0
Bank Sta=5017,5021.9
XS Rating Curve= 0 ,0
Exp/Cntr=0.3,0.1

Type RM Length L Ch R = 1 ,51960   ,124,124,124
BEGIN DESCRIPTION:
Mapping XS 74306d14
END DESCRIPTION:
XS GIS Cut Line= 5
      1573065.36       6806247.9       1573317.1      6806239.22
      1573523.26      6806219.69      1573714.24      6806065.61
        1573785.      6805981.98
#Sta/Elev= 30
    4662  1866.6  4691.7 1865.22  4741.7 1864.22  4941.9 1862.88    4952 1862.36
    4962 1860.44  4969.6 1859.96  4969.9 1859.46  4974.1 1859.46  4974.5 1859.96
  4978.5 1861.38  4983.5 1860.23  4992.1 1862.14  5002.2 1863.37  5012.2  1862.6
  5042.4 1863.21  5081.7 1862.67  5086.7 1863.65  5102.6 1863.02  5112.7 1864.04
  5130.6 1863.66  5223.4 1864.46  5251.7 1865.26    5265 1866.26  5301.7 1866.53
  5343.4 1868.41  5372.5  1868.3  5415.4 1868.94  5442.8 1870.12  5475.9 1870.19
#Mann= 3 ,-1 , 0
    4662     .05       0  4969.6     .05       0  4974.5     .05       0
Bank Sta=4969.6,4974.5
XS Rating Curve= 0 ,0
Exp/Cntr=0.3,0.1

Type RM Length L Ch R = 1 ,51836   ,130,130,130
BEGIN DESCRIPTION:
Mapping XS 0df2fb67
END DESCRIPTION:
XS GIS Cut Line= 5
      1573069.69      6806306.49        1573252.      6806323.86
      1573486.37      6806319.52      1573610.07      6806230.54
      1573794.41      6806002.82
#Sta/Elev= 30
  4748.4 1866.58  4773.8 1864.59    4824 1863.33  4944.5 1863.55  4973.7 1861.61
  4978.7 1862.14  4984.5  1860.8  4994.5 1861.51  5004.5 1864.18  5014.5  1863.9
  5034.5 1857.63  5042.1 1856.95  5042.4 1856.45  5046.6 1856.45    5047 1856.95
  5054.6 1857.12  5074.6 1861.59  5094.6 1862.71  5224.1 1862.36  5230.2 1862.97
  5295.3 1862.78  5380.6 1864.89  5401.4 1864.65  5423.8 1866.24  5473.3 1866.84
  5494.2 1867.51  5508.5 1868.66  5529.3 1867.85  5601.2  1870.3  5611.3 1869.87
#Mann= 3 ,-1 , 0
  4748.4     .05       0  5042.1     .05       0    5047     .05       0
Bank Sta=5042.1,5047
XS Rating Curve= 0 ,0
Exp/Cntr=0.3,0.1

Type RM Length L Ch R = 1 ,51706   ,102,102,102
BEGIN DESCRIPTION:
Mapping XS a533d139
END DESCRIPTION:
XS GIS Cut Line= 5
      1573071.88      6806419.34      1573327.95      6806430.19
      1573473.35      6806386.79      1573599.22      6806295.64
      1573780.75      6806047.12
#Sta/Elev= 30
  4815.2  1866.4  4828.3 1865.34  4897.5 1863.38  4968.5 1863.05  4998.5 1859.18
    5016 1858.23  5016.4 1857.73    5021 1858.23  5071.5 1862.22  5095.6 1866.33
  5110.2 1867.28  5151.9    1867  5172.8 1867.91  5193.7 1867.23  5200.2 1866.71
  5205.4 1864.28  5226.5 1864.34  5230.6 1862.68  5237.6 1862.24    5287 1861.63
  5295.5 1860.89  5337.3 1862.09  5345.8 1861.43    5352 1862.43  5401.8 1862.11
  5524.3 1864.55  5546.2 1865.99  5596.4  1866.7  5638.1 1868.63  5686.4 1868.88
#Mann= 3 ,-1 , 0
  4815.2     .05       0    5016     .05       0    5021     .05       0
Bank Sta=5016,5021
XS Rating Curve= 0 ,0
Exp/Cntr=0.3,0.1

Type RM Length L Ch R = 1 ,51604   ,101,101,101
BEGIN DESCRIPTION:
Mapping XS 96547cce
END DESCRIPTION:
XS GIS Cut Line= 5
      1573067.49      6806547.39      1573325.78      6806510.49
      1573488.54      6806441.04      1573638.28       6806306.5
       1573803.2      6806054.78
#Sta/Elev= 30
  4761.9 1867.21  4935.2 1863.85  4951.3 1861.36  4971.5 1856.08  4989.2 1855.24
  4989.6 1854.74  4994.2 1855.24  5025.1 1856.32  5069.1 1861.14  5076.3  1863.5
  5098.2 1866.97  5121.8 1868.86  5163.3 1868.51    5185 1867.57  5213.5 1865.54
    5221 1863.88  5235.2 1862.12  5248.8 1861.19  5256.1  1861.9  5270.3 1861.33
  5291.2 1861.98    5348 1861.02  5434.9 1862.19  5506.9 1864.56  5542.7 1864.55
  5585.6 1866.72  5591.6 1866.08  5614.5 1866.67  5650.3 1868.47    5702  1868.7
#Mann= 3 ,-1 , 0
  4761.9     .05       0  4989.2     .05       0  4994.2     .05       0
Bank Sta=4989.2,4994.2
XS Rating Curve= 0 ,0
Exp/Cntr=0.3,0.1

Type RM Length L Ch R = 1 ,51503   ,120,120,120
BEGIN DESCRIPTION:
Mapping XS 74d4f605
END DESCRIPTION:
XS GIS Cut Line= 5
      1573108.74      6806896.81      1573393.06      6806519.17
      1573512.41      6806445.38      1573662.15      6806332.54
       1573800.5      6806099.08
#Sta/Elev= 30
  4614.2 1866.73  4882.1  1865.5  4911.2 1863.28  4938.3 1856.18  4985.8 1855.19
  4986.1 1854.69  4990.8 1855.19  5025.7 1855.36  5052.8 1859.18    5082 1861.94
  5084.5 1863.05  5096.9 1863.34  5102.7 1864.82  5139.4 1868.81  5160.6 1868.96
  5183.2 1867.36  5191.4 1865.82  5197.3 1866.68  5206.8 1865.74  5212.7 1862.96
  5218.6 1864.36  5225.8 1862.05    5234  1862.4  5263.1 1860.63  5305.6 1861.78
    5363 1860.43  5587.8 1864.96  5603.4 1866.28  5652.5 1866.85  5686.1 1868.46
#Mann= 3 ,-1 , 0
  4614.2     .05       0  4985.8     .05       0  4990.8     .05       0
Bank Sta=4985.8,4990.8
XS Rating Curve= 0 ,0
Exp/Cntr=0.3,0.1