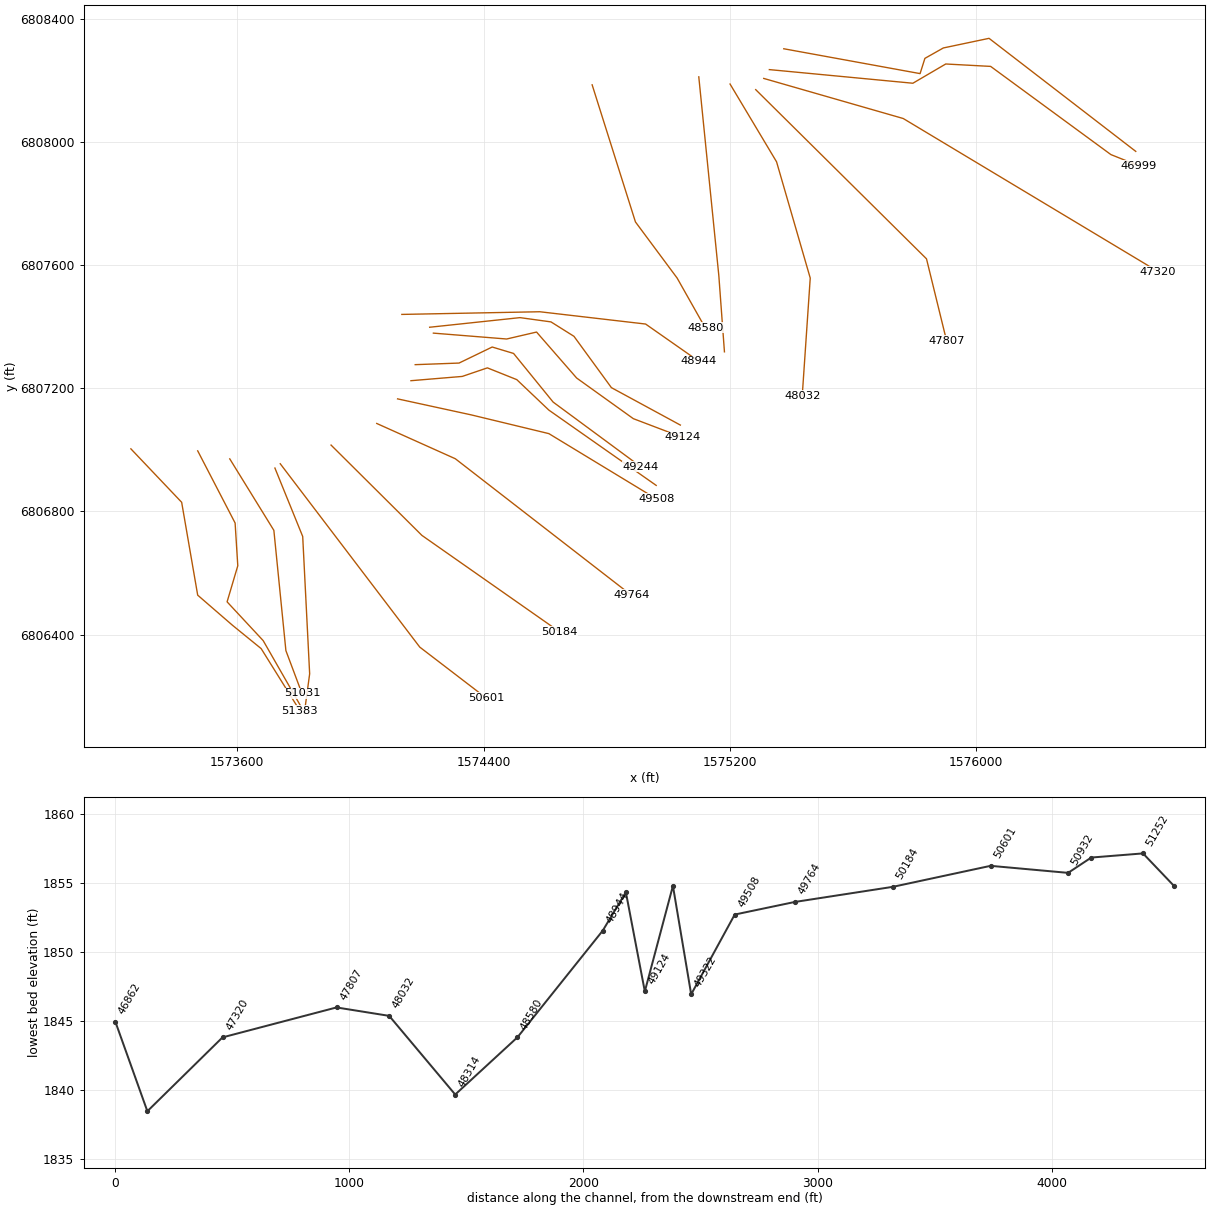
HEC-RAS study Buttonwillow Creek.prj: Buttonwillow Creek Base Level Engineering

--- Buttonwillow Creek.g01 (geometry) --- (continued)

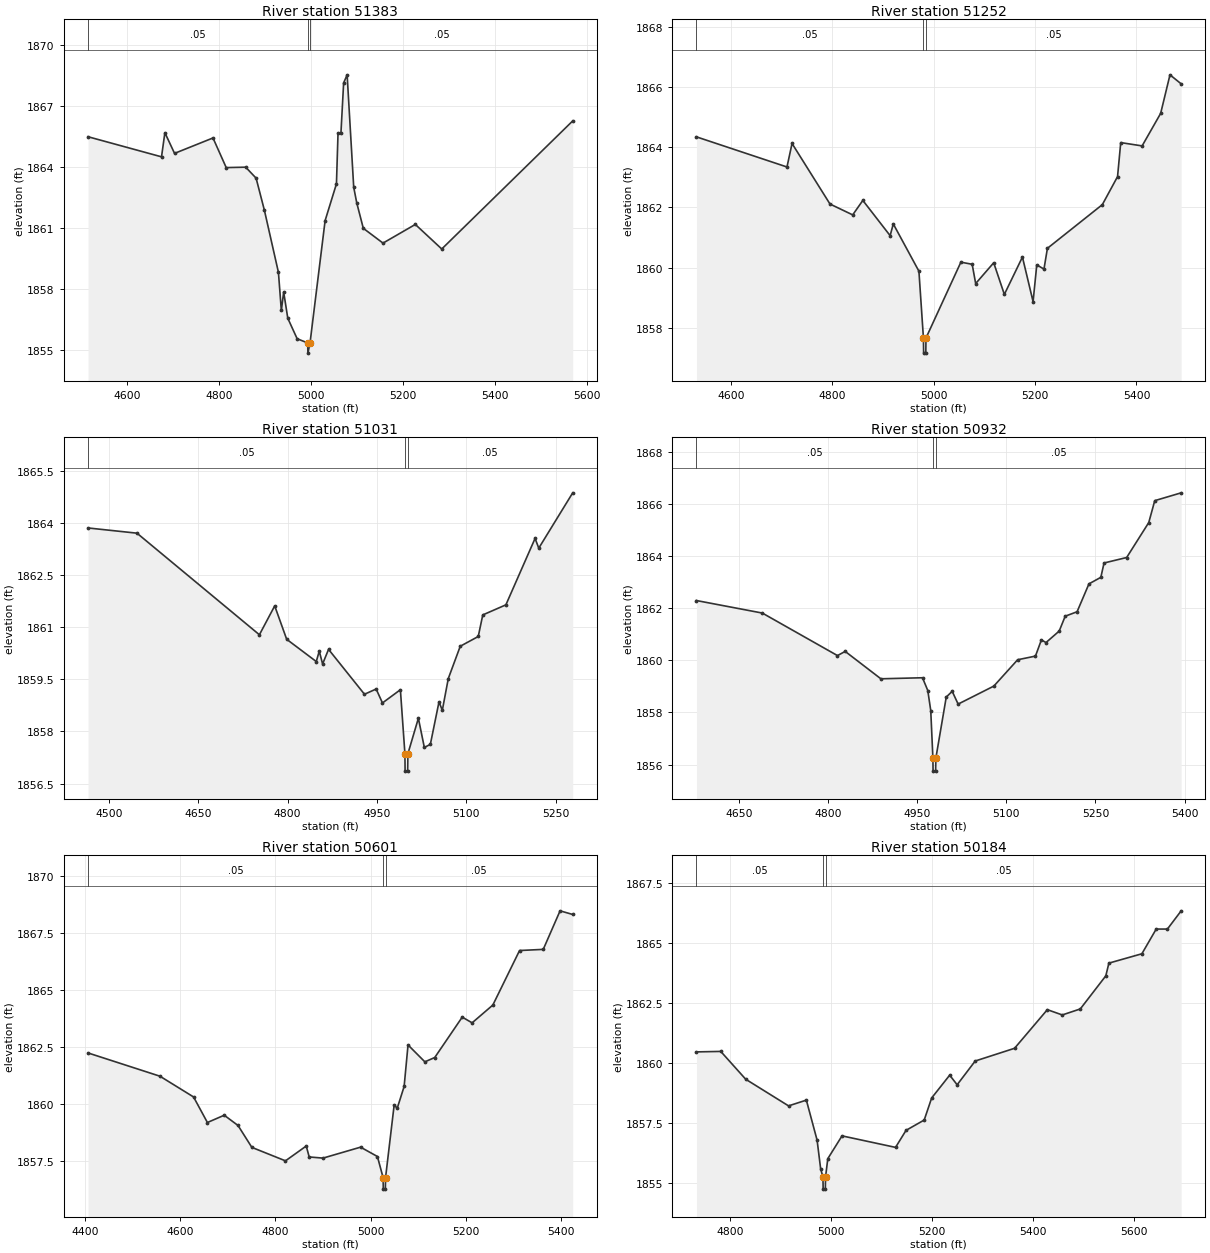
Type RM Length L Ch R = 1 ,51383   ,131,131,131
BEGIN DESCRIPTION:
Mapping XS 01c4119d
END DESCRIPTION:
XS GIS Cut Line= 6
      1573254.19      6807003.08       1573419.1       6806829.5
      1573471.18      6806527.85      1573584.03      6806430.19
      1573677.34      6806354.24      1573803.03      6806152.71
#Sta/Elev= 30
    4516 1865.49  4675.6  1864.5  4682.9 1865.69  4703.9 1864.67  4787.4 1865.43
  4816.1 1863.97  4858.4 1863.99    4881 1863.45    4899 1861.87  4929.5 1858.81
  4935.8 1856.93  4940.9 1857.84  4949.8 1856.55  4970.1 1855.54  4993.1 1855.33
  4993.5 1854.83  4998.1 1855.33  5030.9 1861.36  5055.5 1863.17  5058.9 1865.65
  5065.2 1865.65  5071.1 1868.14  5078.7 1868.54    5093    1863  5099.6 1862.23
  5113.8 1860.98  5156.6 1860.25  5226.8 1861.17  5284.2 1859.96  5568.6 1866.27
#Mann= 3 ,-1 , 0
    4516     .05       0  4993.1     .05       0  4998.1     .05       0
Bank Sta=4993.1,4998.1
XS Rating Curve= 0 ,0
Exp/Cntr=0.3,0.1

Type RM Length L Ch R = 1 ,51252   ,221,221,221
BEGIN DESCRIPTION:
Mapping XS 39e4522d
END DESCRIPTION:
XS GIS Cut Line= 6
       1573471.2      6806996.57      1573592.71      6806762.22
      1573601.39      6806623.34      1573566.67      6806506.15
      1573683.85      6806380.28      1573811.89      6806156.77
#Sta/Elev= 30
  4531.6 1864.34  4710.2 1863.34  4720.2 1864.12  4795.1 1862.11  4839.9 1861.75
  4859.9 1862.23  4913.8 1861.06    4920 1861.45  4970.6 1859.88  4979.5 1857.66
  4979.9 1857.16  4984.2 1857.16  4984.5 1857.66  5053.4 1860.18  5075.7 1860.11
  5082.6 1859.47  5118.2 1860.16  5139.2 1859.11  5174.9 1860.35  5195.9 1858.87
  5203.2 1860.09  5217.4 1859.95  5224.2 1860.64  5332.6 1862.09  5362.6 1863.02
  5368.9 1864.15  5411.1 1864.04  5447.7 1865.12  5466.1  1866.4  5488.2  1866.1
#Mann= 3 ,-1 , 0
  4531.6     .05       0  4979.5     .05       0  4984.5     .05       0
Bank Sta=4979.5,4984.5
XS Rating Curve= 0 ,0
Exp/Cntr=0.3,0.1

Type RM Length L Ch R = 1 ,51031   ,99,99,99
BEGIN DESCRIPTION:
Mapping XS ca48cdbc
END DESCRIPTION:
XS GIS Cut Line= 4
      1573575.36      6806970.54      1573718.58      6806738.35
      1573757.64      6806347.73      1573809.72      6806208.85
#Sta/Elev= 30
  4465.1 1863.85  4547.3  1863.7  4752.8 1860.78  4778.5 1861.61  4798.6 1860.65
  4848.3 1860.01  4853.3 1860.31  4858.9 1859.94  4868.9 1860.36  4929.2 1859.07
  4948.8 1859.22  4959.4 1858.82  4989.5  1859.2  4997.1 1857.36  4997.4 1856.86
  5001.7 1856.86  5002.1 1857.36  5019.7 1858.38  5029.7 1857.54  5039.8 1857.63
  5054.3 1858.85  5059.9 1858.61  5069.9 1859.52    5090 1860.45  5120.2 1860.73
  5127.8 1861.35  5166.6 1861.64  5215.6 1863.55  5221.8 1863.27  5278.8 1864.86
#Mann= 3 ,-1 , 0
  4465.1     .05       0  4997.1     .05       0  5002.1     .05       0
Bank Sta=4997.1,5002.1
XS Rating Curve= 0 ,0
Exp/Cntr=0.3,0.1

Type RM Length L Ch R = 1 ,50932   ,331,331,331
BEGIN DESCRIPTION:
Mapping XS 89adafc8
END DESCRIPTION:
XS GIS Cut Line= 4
      1573721.97      6806940.73      1573812.24      6806718.52
      1573834.81      6806272.34      1573817.46      6806143.91
#Sta/Elev= 30
  4578.1 1862.29    4689 1861.81  4815.5 1860.18  4828.5 1860.34  4888.6 1859.29
  4958.7 1859.33  4967.6 1858.84  4972.6 1858.07  4976.2 1856.25  4976.5 1855.75
  4980.8 1855.75  4981.2 1856.25  4998.7 1858.59  5008.7 1858.81  5018.7 1858.32
  5078.8 1859.01  5118.9 1860.02  5148.9 1860.16  5158.9 1860.78  5166.7 1860.68
  5188.9 1861.12    5199 1861.69    5219 1861.86    5239 1862.93    5259 1863.18
  5264.4 1863.73  5302.5 1863.94  5339.7 1865.28  5349.8 1866.12  5394.3 1866.42
#Mann= 3 ,-1 , 0
  4578.1     .05       0  4976.2     .05       0  4981.2     .05       0
Bank Sta=4976.2,4981.2
XS Rating Curve= 0 ,0
Exp/Cntr=0.3,0.1

Type RM Length L Ch R = 1 ,50601   ,417,417,417
BEGIN DESCRIPTION:
Mapping XS 387a894d
END DESCRIPTION:
XS GIS Cut Line= 3
      1573739.32      6806954.63      1574192.45      6806359.14
      1574407.75       6806194.2
#Sta/Elev= 30
  4405.7 1862.23    4557 1861.21  4627.7  1860.3  4656.8 1859.18  4692.2  1859.5
  4721.2 1859.05  4750.3 1858.09    4821  1857.5  4864.7 1858.15  4870.9 1857.67
    4900 1857.62    4979  1858.1  5014.4 1857.69  5026.4 1856.76  5026.8 1856.26
  5031.1 1856.26  5031.5 1856.76  5049.7 1859.96    5056  1859.8  5070.6 1860.76
  5078.8 1862.58  5114.2 1861.84    5135 1862.03  5192.8  1863.8  5213.6 1863.55
  5257.2 1864.33  5313.4 1866.72  5363.2 1866.77  5398.6 1868.46  5425.2  1868.3
#Mann= 3 ,-1 , 0
  4405.7     .05       0  5026.4     .05       0  5031.5     .05       0
Bank Sta=5026.4,5031.5
XS Rating Curve= 0 ,0
Exp/Cntr=0.3,0.1

Type RM Length L Ch R = 1 ,50184   ,420,420,420
BEGIN DESCRIPTION:
Mapping XS 034cc318
END DESCRIPTION:
XS GIS Cut Line= 3
      1573904.29      6807015.36      1574199.39      6806721.99
      1574645.54      6806409.52
#Sta/Elev= 30
  4732.6 1860.46  4780.7 1860.48  4830.2 1859.32  4915.1 1858.21  4950.4 1858.45
  4971.7 1856.78  4978.7 1855.59  4983.3 1855.24  4983.7 1854.74    4988 1854.74
  4988.4 1855.24  4992.9 1856.01  5021.1 1856.96  5127.2 1856.48    5148 1857.19
    5184 1857.62  5198.8 1858.54  5234.5 1859.49  5249.3 1859.09  5285.1 1860.08
  5363.1 1860.61  5428.1 1862.22  5457.7    1862  5493.4 1862.25    5544 1863.63
  5550.1 1864.16  5615.5 1864.55  5643.9 1865.58  5666.1 1865.58  5693.4 1866.34
#Mann= 3 ,-1 , 0
  4732.6     .05       0  4983.3     .05       0  4988.4     .05       0
Bank Sta=4983.3,4988.4
XS Rating Curve= 0 ,0
Exp/Cntr=0.3,0.1

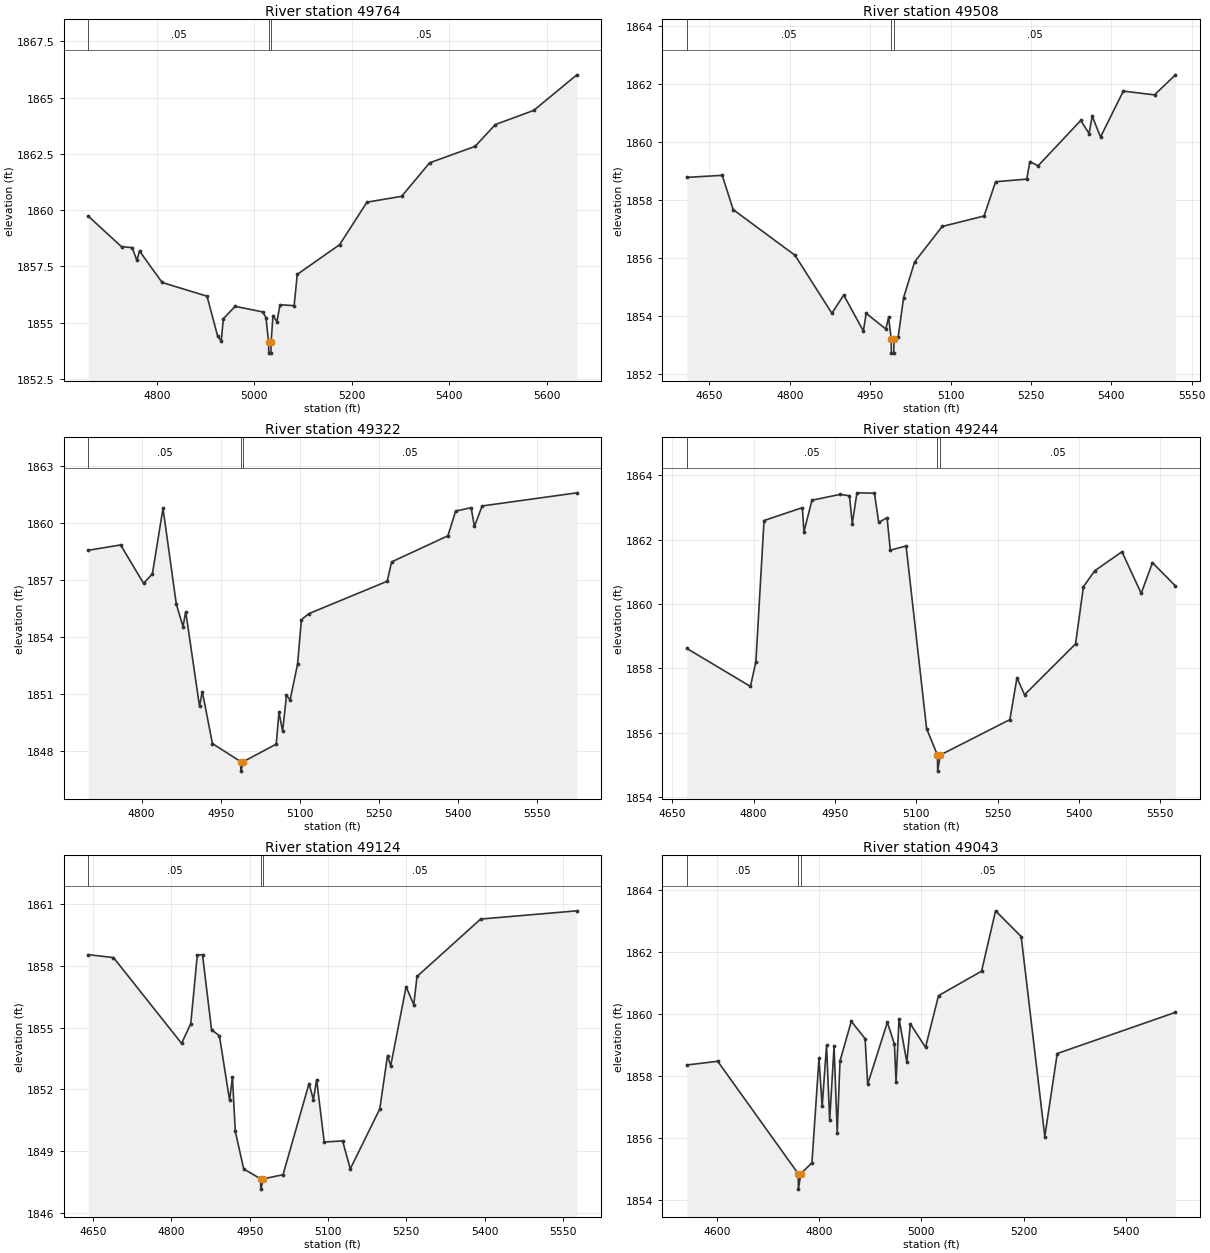
Type RM Length L Ch R = 1 ,49764   ,256,256,256
BEGIN DESCRIPTION:
Mapping XS 0b50cb25
END DESCRIPTION:
XS GIS Cut Line= 3
      1574052.71      6807085.52       1574307.9      6806970.95
      1574879.09      6806528.24
#Sta/Elev= 30
  4659.5 1859.73  4727.8 1858.37  4749.7 1858.33  4759.3 1857.76  4764.7 1858.18
  4811.1 1856.78  4903.2 1856.17  4925.1 1854.39  4932.4 1854.18  4936.7 1855.17
  4960.9 1855.72  5017.7 1855.47  5024.1 1855.22  5029.5 1854.14  5029.9 1853.64
  5034.3 1853.64  5034.7 1854.14  5038.5 1855.31  5046.6 1855.04    5053 1855.79
  5081.9 1855.75  5088.3 1857.14  5175.2 1858.46  5231.3 1860.35  5302.5 1860.61
  5359.9  1862.1  5453.1 1862.83  5494.7  1863.8  5573.5 1864.43  5661.9 1866.01
#Mann= 3 ,-1 , 0
  4659.5     .05       0  5029.5     .03       0  5034.7     .05       0
Bank Sta=5029.5,5034.7
XS Rating Curve= 0 ,0
Exp/Cntr=0.3,0.1

Type RM Length L Ch R = 1 ,49508   ,186,186,186
BEGIN DESCRIPTION:
Mapping XS a6cb575f
END DESCRIPTION:
XS GIS Cut Line= 4
      1574120.38       6807165.4      1574359.98      6807113.31
      1574611.72      6807052.55      1574960.36      6806840.93
#Sta/Elev= 30
  4607.7 1858.78  4673.8 1858.85  4694.3 1857.67  4809.6  1856.1  4878.6  1854.1
  4900.6 1854.73  4937.3 1853.49  4942.5  1854.1  4979.2 1853.56  4984.4 1853.96
  4989.2 1853.23  4989.6 1852.73    4994 1852.73  4994.4 1853.23  5002.1 1853.27
  5012.4 1854.64  5032.9 1855.87  5084.4 1857.09  5162.5 1857.45  5184.1 1858.63
  5242.2 1858.72  5248.1 1859.32  5263.5 1859.18    5343 1860.74  5358.5 1860.29
  5364.4 1860.89  5379.9 1860.17  5422.5 1861.75  5480.7 1861.62  5519.7 1862.31
#Mann= 3 ,-1 , 0
  4607.7     .05       0  4989.2     .05       0  4994.4     .05       0
Bank Sta=4989.2,4994.4
XS Rating Curve= 0 ,0
Exp/Cntr=0.3,0.1

Type RM Length L Ch R = 1 ,49322   ,78,78,78
BEGIN DESCRIPTION:
Mapping XS 7b7ff044
END DESCRIPTION:
XS GIS Cut Line= 6
      1574163.79      6807224.42      1574330.47      6807238.31
      1574412.07      6807266.09      1574507.55      6807227.89
      1574611.72      6807128.94      1574960.33      6806884.37
#Sta/Elev= 30
    4699 1858.56  4760.4 1858.84  4803.9 1856.82  4820.6 1857.32  4840.7 1860.77
    4866 1855.72  4878.6 1854.55  4883.8 1855.33  4909.9 1850.36  4915.2 1851.13
  4934.4  1848.4  4987.9 1847.45  4988.3 1846.95  4993.1 1847.45  5055.3 1848.37
  5060.5 1850.05  5067.4 1849.05  5074.7 1850.93  5081.6  1850.7  5095.7 1852.57
    5103 1854.91  5117.2 1855.23  5265.5 1856.93    5274 1857.95  5380.6 1859.32
  5395.3 1860.62  5424.7  1860.8  5430.8 1859.81  5445.5 1860.89    5625 1861.58
#Mann= 3 ,-1 , 0
    4699     .05       0  4987.9     .05       0  4993.1     .05       0
Bank Sta=4987.9,4993.1
XS Rating Curve= 0 ,0
Exp/Cntr=0.3,0.1

Type RM Length L Ch R = 1 ,49244   ,120,120,120
BEGIN DESCRIPTION:
Mapping XS 8dbba095
END DESCRIPTION:
XS GIS Cut Line= 6
      1574177.67       6807276.5      1574320.05      6807281.71
      1574427.69       6807333.8      1574497.14      6807312.96
      1574625.61      6807154.98      1574910.17      6806945.03
#Sta/Elev= 30
  4676.8 1858.62  4794.2 1857.44  4804.2  1858.2  4819.3 1862.59    4890 1862.99
  4892.9 1862.24  4907.6 1863.22  4959.2  1863.4  4976.8 1863.36    4982 1862.49
  4990.6 1863.45  5022.9 1863.44  5030.8 1862.53  5046.2 1862.68  5052.2 1861.67
  5081.3  1861.8  5119.1 1856.13  5139.1 1855.31  5139.5 1854.81  5144.3 1855.31
  5272.7 1856.41  5285.8 1857.71  5299.7 1857.18  5393.8 1858.76  5408.4 1860.54
  5429.2 1861.03  5479.4 1861.62  5514.9 1860.33  5535.7 1861.28    5578 1860.56
#Mann= 3 ,-1 , 0
  4676.8     .05       0  5139.1     .05       0  5144.3     .05       0
Bank Sta=5139.1,5144.3
XS Rating Curve= 0 ,0
Exp/Cntr=0.3,0.1

Type RM Length L Ch R = 1 ,49124   ,81,81,81
BEGIN DESCRIPTION:
Mapping XS 905b51a3
END DESCRIPTION:
XS GIS Cut Line= 6
      1574236.71      6807378.94      1574474.57      6807359.84
      1574571.79      6807382.41        1574702.       6807233.1
      1574886.03      6807101.16      1575045.73       6807040.4
#Sta/Elev= 30
  4640.6 1858.55    4689 1858.41  4819.5 1854.24  4837.1  1855.2  4849.6 1858.53
  4859.6 1858.55  4876.9  1854.9    4892 1854.61  4911.5 1851.47  4916.9 1852.61
  4922.4 1849.97  4938.5 1848.14  4970.9 1847.66  4971.3 1847.16  4976.1 1847.66
  5013.9 1847.86  5063.7 1852.29    5072 1851.51  5078.3 1852.47  5092.8 1849.45
  5128.1  1849.5  5142.7 1848.14  5199.3 1851.06  5214.1 1853.65  5220.2 1853.15
  5249.7 1856.99  5264.4 1856.12  5270.6 1857.49  5392.5 1860.28  5576.9 1860.68
#Mann= 3 ,-1 , 0
  4640.6     .05       0  4970.9     .05       0  4976.1     .05       0
Bank Sta=4970.9,4976.1
XS Rating Curve= 0 ,0
Exp/Cntr=0.3,0.1

Type RM Length L Ch R = 1 ,49043   ,99,99,99
BEGIN DESCRIPTION:
Mapping XS 9d7b912a
END DESCRIPTION:
XS GIS Cut Line= 6
      1574224.56      6807398.03      1574517.97      6807429.28
      1574618.66      6807415.39      1574693.32      6807368.52
      1574814.85      6807201.85      1575038.79      6807080.33
#Sta/Elev= 30
  4541.3 1858.36  4601.8 1858.48  4759.2 1854.85  4759.6 1854.35  4764.4 1854.85
  4786.1  1855.2  4799.9 1858.57  4806.1 1857.02  4814.7    1859  4820.8 1856.57
  4829.4 1858.96  4835.6 1856.17    4841 1858.49  4863.1 1859.77  4890.1 1859.21
  4895.1 1857.74  4933.7 1859.74  4947.5 1859.03  4950.6  1857.8  4956.5 1859.85
  4971.8 1858.45  4978.6 1859.69  5008.3 1858.93  5033.7  1860.6  5117.9 1861.39
  5145.3 1863.34  5195.4 1862.51  5241.6 1856.05  5265.9 1858.73  5497.1 1860.06
#Mann= 3 ,-1 , 0
  4541.3     .05       0  4759.2     .05       0  4764.4     .05       0
Bank Sta=4759.2,4764.4
XS Rating Curve= 0 ,0
Exp/Cntr=0.3,0.1

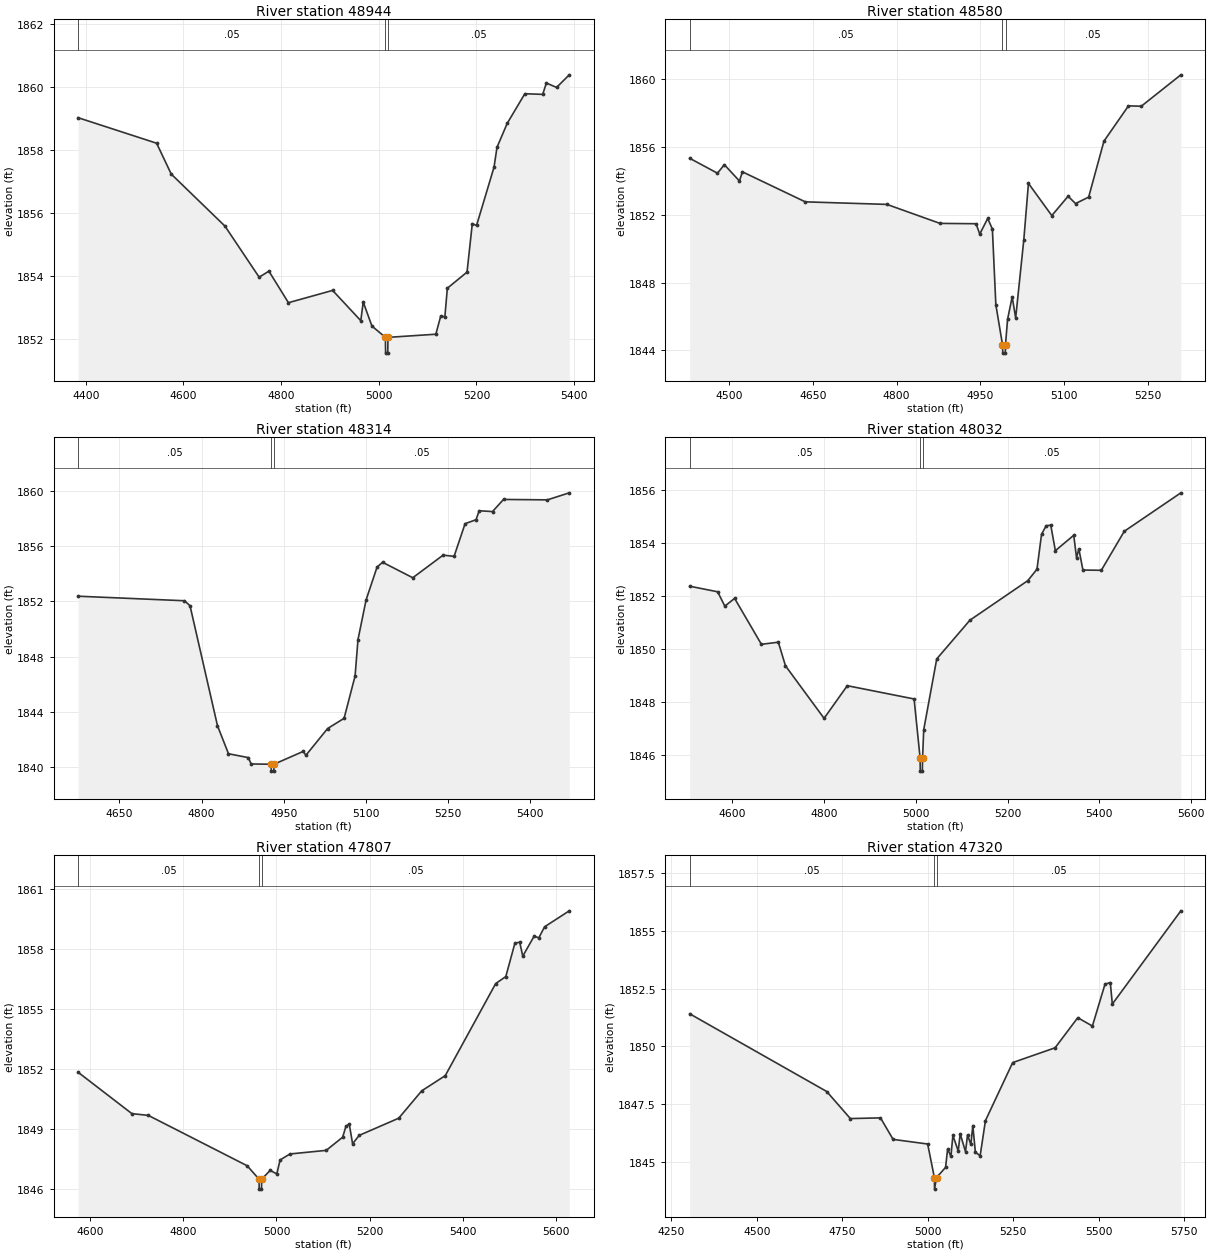
Type RM Length L Ch R = 1 ,48944   ,364,364,364
BEGIN DESCRIPTION:
Mapping XS 3cdb5273
END DESCRIPTION:
XS GIS Cut Line= 4
      1574134.27       6807439.7      1574582.21      6807448.38
      1574925.96      6807408.45      1575099.57      6807286.92
#Sta/Elev= 30
  4384.2 1859.03    4545 1858.22    4575 1857.24    4685 1855.59    4755 1853.97
    4775 1854.16    4815 1853.16  4905.5 1853.55  4963.2 1852.59  4968.2 1853.18
    4986 1852.42  5013.6 1852.06    5014 1851.56  5018.4 1851.56  5018.9 1852.06
  5116.9 1852.16    5127 1852.74  5135.4 1852.71  5140.5 1853.62  5180.8 1854.13
  5191.6 1855.67  5200.3 1855.61  5236.1 1857.46  5242.2 1858.09  5263.1 1858.85
  5299.2 1859.79  5335.8 1859.77  5343.3 1860.13  5364.2 1859.99  5390.2 1860.39
#Mann= 3 ,-1 , 0
  4384.2     .05       0  5013.6     .03       0  5018.9     .05       0
Bank Sta=5013.6,5018.9
XS Rating Curve= 0 ,0
Exp/Cntr=0.3,0.1

Type RM Length L Ch R = 1 ,48580   ,266,266,266
BEGIN DESCRIPTION:
Mapping XS eca54c04
END DESCRIPTION:
XS GIS Cut Line= 4
      1574752.33       6808185.4      1574892.97      6807740.05
      1575028.39      6807557.76      1575119.52      6807396.32
#Sta/Elev= 30
  4429.5 1855.33  4479.2 1854.45  4491.6 1854.95  4518.6 1853.99  4523.9 1854.53
  4636.5 1852.76  4782.6 1852.61  4877.7 1851.49  4942.3 1851.47  4948.9 1850.86
  4963.1 1851.78  4971.5 1851.16  4977.7  1846.7  4989.6 1844.34  4990.1 1843.84
  4994.6 1843.84    4995 1844.34  4998.7 1845.83    5007 1847.16  5013.2 1845.91
  5027.8 1850.53  5036.1 1853.85  5077.9 1851.95  5107.1 1853.09  5120.4 1852.66
  5143.9 1853.04  5171.3 1856.34  5215.2 1858.42  5238.2  1858.4    5309 1860.25
#Mann= 3 ,-1 , 0
  4429.5     .05       0  4989.6     .05       0    4995     .05       0
Bank Sta=4989.6,4995
XS Rating Curve= 0 ,0
Exp/Cntr=0.3,0.1

Type RM Length L Ch R = 1 ,48314   ,282,282,282
BEGIN DESCRIPTION:
Mapping XS 0cb72a11
END DESCRIPTION:
XS GIS Cut Line= 3
       1575098.7      6808211.35       1575163.8      6807565.57
      1575182.03       6807318.2
#Sta/Elev= 30
  4574.4 1852.38  4768.7 1852.05  4778.8 1851.69    4829 1842.98  4849.1 1840.95
  4885.4 1840.67  4890.4 1840.21  4926.8 1840.19  4927.3 1839.69  4931.8 1839.69
  4932.2 1840.19  4985.5 1841.12  4990.5 1840.84  5030.1 1842.78  5060.2 1843.52
  5080.3 1846.59  5085.6 1849.23  5100.4 1852.11  5120.5  1854.5  5130.6 1854.84
  5185.7 1853.72  5241.1 1855.36  5261.1 1855.27  5281.2 1857.64  5301.2 1857.93
    5307 1858.58  5331.3 1858.52  5351.4  1859.4  5431.6 1859.37  5471.5 1859.88
#Mann= 3 ,-1 , 0
  4574.4     .05       0  4926.8     .05       0  4932.2     .05       0
Bank Sta=4926.8,4932.2
XS Rating Curve= 0 ,0
Exp/Cntr=0.3,0.1

Type RM Length L Ch R = 1 ,48032   ,225,225,225
BEGIN DESCRIPTION:
Mapping XS d5863b14
END DESCRIPTION:
XS GIS Cut Line= 4
      1575200.24        6808188.       1575351.3      6807935.36
      1575460.68      6807557.76      1575434.64      6807174.93
#Sta/Elev= 30
  4506.8 1852.36  4567.8 1852.15  4583.4 1851.61  4604.8  1851.9  4663.2 1850.17
  4700.1 1850.25  4715.7 1849.36  4799.9 1847.38  4850.5 1848.61  4996.2 1848.11
  5009.3 1845.89  5009.7 1845.39  5014.2 1845.39  5014.7 1845.89  5017.2 1846.95
  5045.6 1849.62    5118 1851.08  5244.2 1852.57  5264.2    1853  5274.2 1854.32
  5284.3 1854.64  5294.3 1854.66  5304.3  1853.7  5344.4 1854.28  5350.5 1853.43
  5355.5 1853.77  5364.4 1852.97  5404.5 1852.96  5454.6 1854.43    5578 1855.88
#Mann= 3 ,-1 , 0
  4506.8     .05       0  5009.3     .05       0  5014.7     .05       0
Bank Sta=5009.3,5014.7
XS Rating Curve= 0 ,0
Exp/Cntr=0.3,0.1

Type RM Length L Ch R = 1 ,47807   ,487,487,487
BEGIN DESCRIPTION:
Mapping XS 4d271a92
END DESCRIPTION:
XS GIS Cut Line= 3
      1575283.57      6808169.76      1575838.28      6807620.26
      1575903.39      6807354.62
#Sta/Elev= 30
  4574.2 1851.85  4689.6 1849.78    4725 1849.69  4937.1 1847.17  4962.5  1846.5
    4963    1846  4967.8    1846  4968.3  1846.5  4986.6 1846.94  5000.7 1846.76
  5007.8 1847.46    5029 1847.76  5106.8 1847.94  5142.1  1848.6  5149.2 1849.15
  5156.3 1849.25  5163.4 1848.27  5177.5 1848.69  5262.4 1849.55  5311.8 1850.92
  5362.3 1851.68  5470.6 1856.29  5492.3 1856.64  5511.8 1858.31  5522.1 1858.36
  5528.7 1857.66    5553 1858.66  5563.2 1858.58  5575.5 1859.13  5628.5 1859.93
#Mann= 3 ,-1 , 0
  4574.2     .05       0  4962.5     .05       0  4968.3     .05       0
Bank Sta=4962.5,4968.3
XS Rating Curve= 0 ,0
Exp/Cntr=0.3,0.1

Type RM Length L Ch R = 1 ,47320   ,321,321,321
BEGIN DESCRIPTION:
Mapping XS a24a832c
END DESCRIPTION:
XS GIS Cut Line= 3
      1575309.68      6808206.18      1575762.76      6808075.98
      1576590.42      6807578.87
#Sta/Elev= 30
    4304 1851.41  4704.9 1848.05    4774 1846.88  4862.2 1846.91  4899.1 1845.98
  5000.2 1845.78  5019.8 1844.33  5020.3 1843.83  5026.1 1844.33  5052.6 1844.77
  5058.5 1845.56  5068.2 1845.25    5074 1846.15  5089.6 1845.48  5095.4 1846.22
  5110.9 1845.45  5116.8 1846.17  5126.5 1845.76  5132.3 1846.58  5139.7 1845.43
  5153.7 1845.27  5169.2 1846.79  5248.9  1849.3    5373 1849.94  5439.3 1851.24
  5482.1 1850.88    5519 1852.69  5534.5 1852.76  5540.4 1851.83  5740.9 1855.86
#Mann= 3 ,-1 , 0
    4304     .05       0  5019.8     .05       0  5026.1     .05       0
Bank Sta=5019.8,5026.1
XS Rating Curve= 0 ,0
Exp/Cntr=0.3,0.1

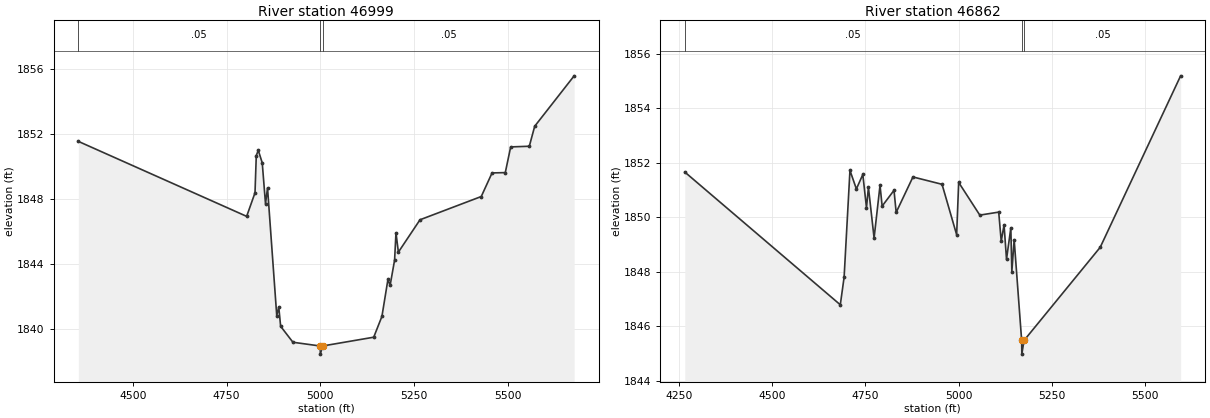
Type RM Length L Ch R = 1 ,46999   ,137,137,137
BEGIN DESCRIPTION:
Mapping XS bc1d93db
END DESCRIPTION:
XS GIS Cut Line= 6
      1575327.83      6808234.84      1575794.01      6808190.57
      1575900.78      6808253.07      1576046.62      6808245.26
      1576437.24       6807958.8      1576527.57      6807922.66
#Sta/Elev= 30
  4354.1 1851.56  4803.3 1846.95  4825.6  1848.4    4829 1850.69  4834.3 1851.01
  4844.9 1850.24  4853.6 1847.72    4859  1848.7  4883.6 1840.85    4889 1841.37
    4894 1840.19  4926.8 1839.21  4999.5 1838.98    5000 1838.48  5005.8 1838.98
  5142.4 1839.52  5164.3  1840.8  5180.4 1843.08  5186.1  1842.7  5198.1 1844.26
  5201.8 1845.94  5208.2 1844.75  5265.9 1846.74  5429.4 1848.17  5458.2 1849.62
  5493.5 1849.64  5507.9 1851.22  5557.6 1851.26    5572 1852.49  5677.3 1855.59
#Mann= 3 ,-1 , 0
  4354.1     .05       0  4999.5     .05       0  5005.8     .05       0
Bank Sta=4999.5,5005.8
XS Rating Curve= 0 ,0
Exp/Cntr=0.3,0.1

Type RM Length L Ch R = 1 ,46862   ,53,53,53
BEGIN DESCRIPTION:
Mapping XS 1b215801
END DESCRIPTION:
XS GIS Cut Line= 6
      1575374.77      6808302.54      1575817.45      6808221.82
      1575833.07       6808271.3      1575892.97      6808305.15
      1576041.41       6808336.4      1576517.93      6807969.24
#Sta/Elev= 30
  4265.5 1851.66  4682.5 1846.79  4692.7  1847.8  4708.4 1851.72  4725.6 1851.04
  4742.9 1851.57  4752.7 1850.35  4757.9  1851.1  4773.1 1849.24    4789 1851.17
  4794.7 1850.41  4826.5 1850.99  4832.3 1850.18  4877.3 1851.48  4955.3 1851.21
  4994.5 1849.36  4999.9 1851.28  5056.6 1850.08  5107.3 1850.19    5114 1849.12
  5121.6 1849.72  5128.2 1848.46  5139.8 1849.61  5142.5 1848.01  5148.7 1849.18
  5168.8 1845.48  5169.3 1844.98  5175.1 1845.48  5379.5  1848.9  5595.1 1855.19
#Mann= 3 ,-1 , 0
  4265.5     .05       0  5168.8     .05       0  5175.1     .05       0
Bank Sta=5168.8,5175.1
XS Rating Curve= 0 ,0
Exp/Cntr=0.3,0.1