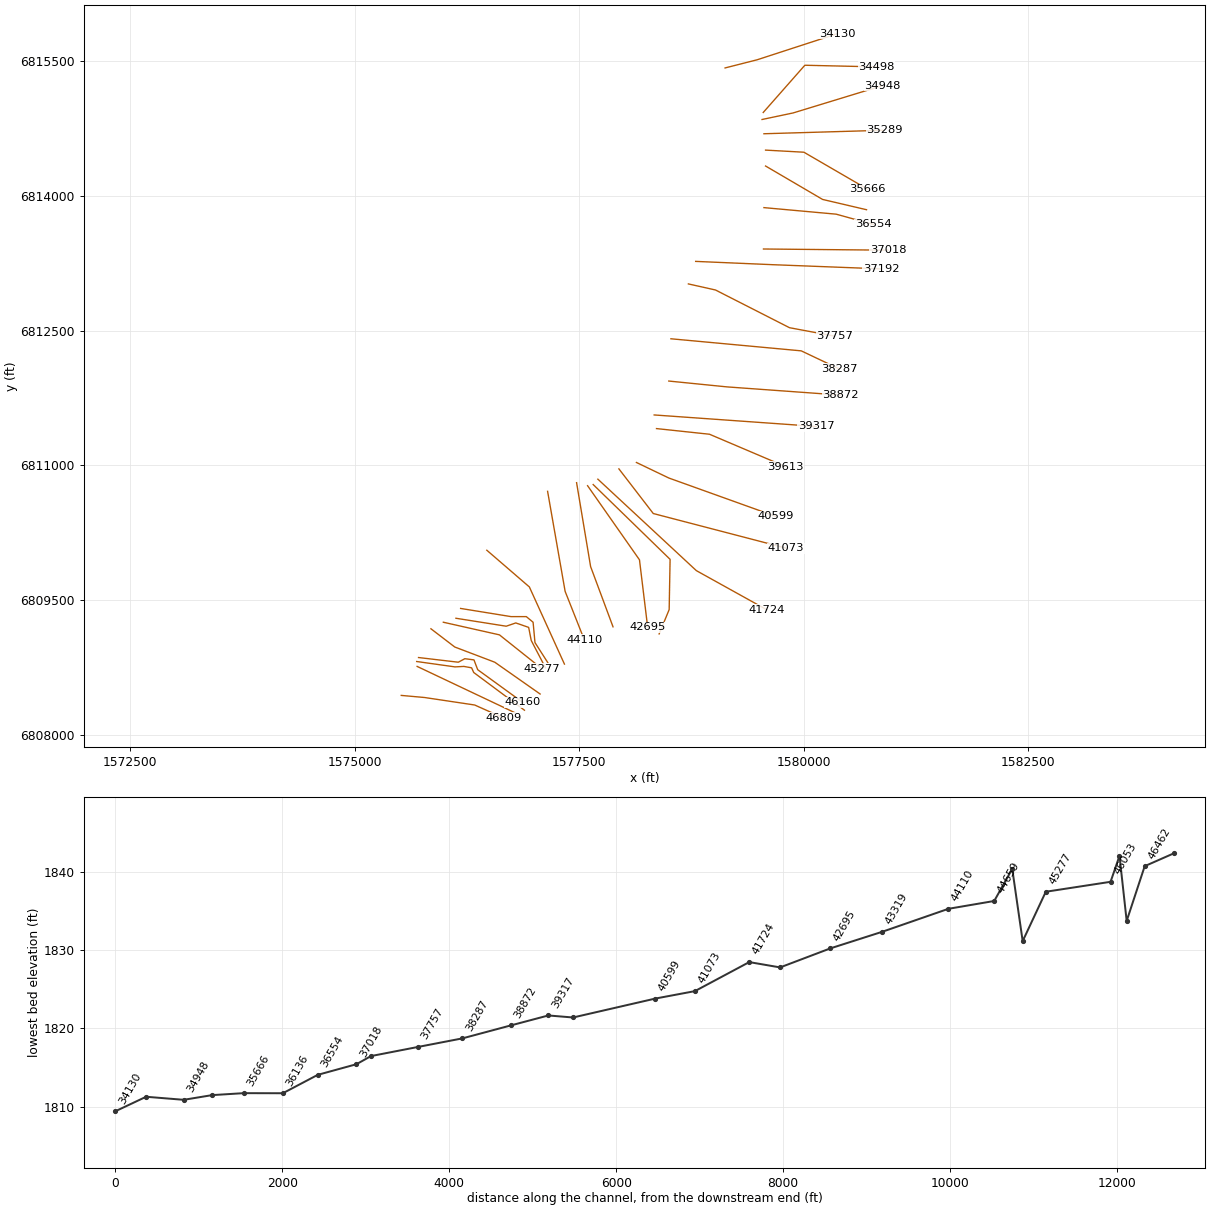
HEC-RAS study Buttonwillow Creek.prj: Buttonwillow Creek Base Level Engineering

--- Buttonwillow Creek.g01 (geometry) --- (continued)

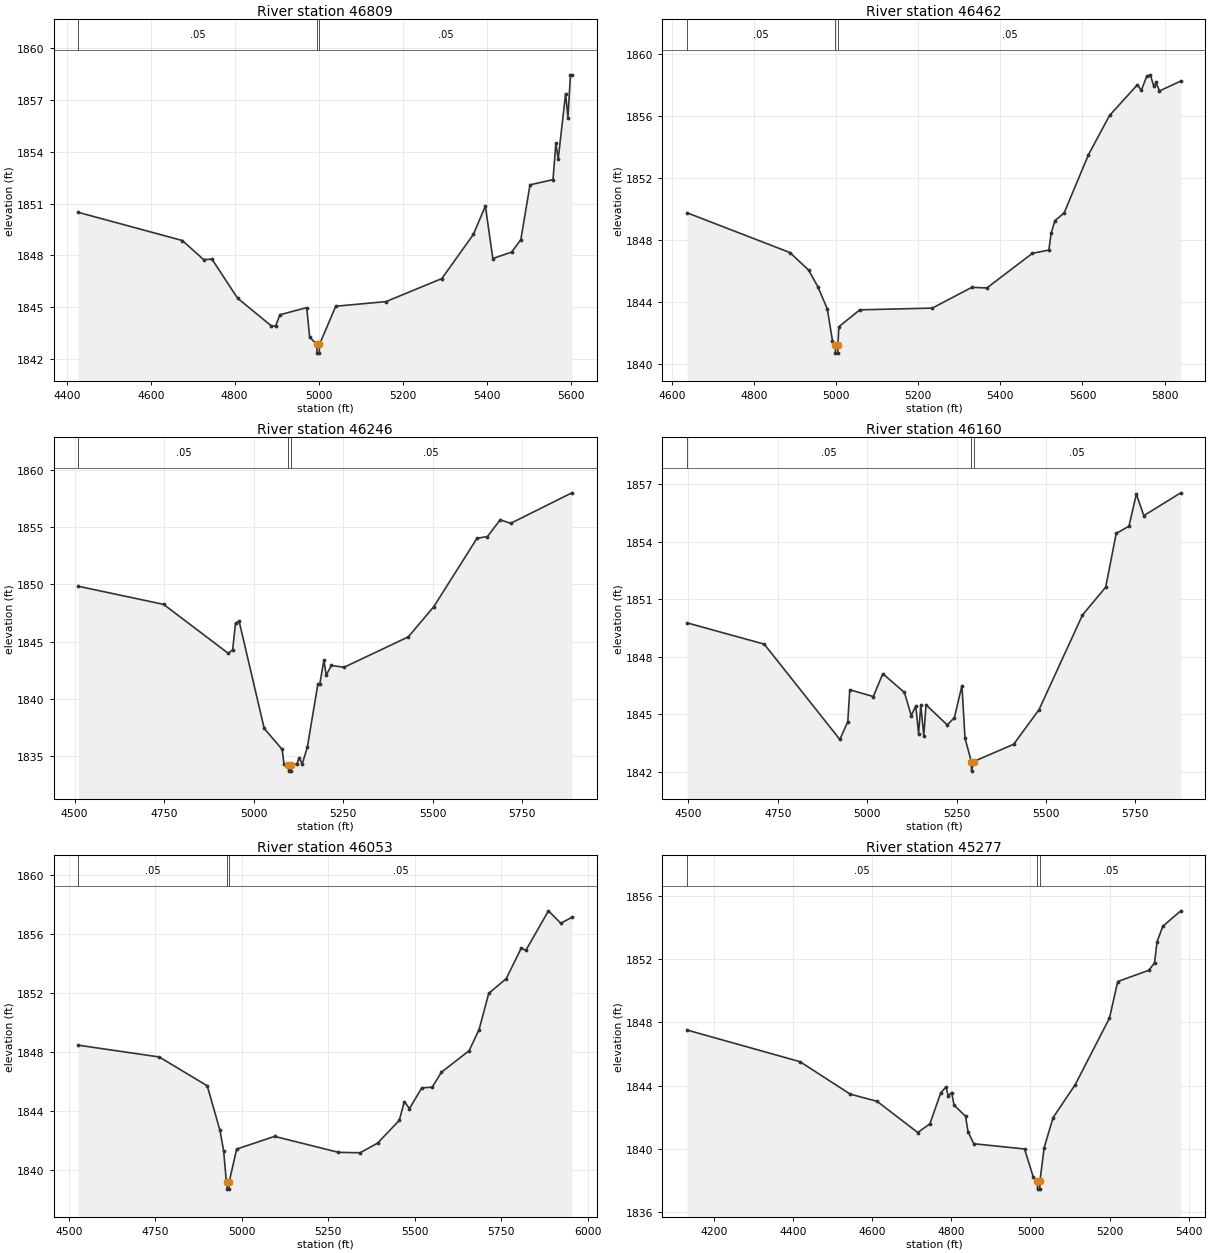
Type RM Length L Ch R = 1 ,46809   ,347,347,347
BEGIN DESCRIPTION:
Mapping XS 7a5ab660
END DESCRIPTION:
XS GIS Cut Line= 4
        1575518.      6808437.96      1575778.39      6808414.53
      1576335.68      6808331.19      1576655.98      6808187.97
#Sta/Elev= 30
  4427.4 1850.49  4675.4 1848.86  4725.9 1847.76  4746.1 1847.78  4806.8 1845.53
  4887.6 1843.92  4897.4 1843.91  4907.9 1844.57  4971.6 1844.98  4978.6 1843.28
  4995.7 1842.85  4996.2 1842.35  5001.5 1842.35    5002 1842.85  5040.8 1845.06
  5160.6 1845.33  5293.4 1846.66  5368.5 1849.21  5397.2 1850.85  5414.9 1847.82
  5459.7 1848.19  5481.6 1848.91  5503.5 1852.08  5558.3 1852.38  5565.1  1854.5
  5570.6 1853.57  5588.3 1857.35  5593.8 1855.97  5599.9 1858.44  5603.2 1858.44
#Mann= 3 ,-1 , 0
  4427.4     .05       0  4995.7     .05       0    5002     .05       0
Bank Sta=4995.7,5002
XS Rating Curve= 0 ,0
Exp/Cntr=0.3,0.1

Type RM Length L Ch R = 1 ,46462   ,216,216,216
BEGIN DESCRIPTION:
Mapping XS 93f5c210
END DESCRIPTION:
XS GIS Cut Line= 2
      1575695.03      6808760.89      1576781.78      6808246.12
#Sta/Elev= 30
  4636.8 1849.76  4887.3  1847.2  4932.8 1846.07  4955.5 1844.99  4978.3 1843.57
  4990.9 1841.53  4997.8 1841.22  4998.3 1840.72  5003.7 1840.72  5004.2 1841.22
  5006.5 1842.42  5057.6 1843.51    5234 1843.62  5330.5 1844.96  5367.1 1844.92
    5478 1847.15    5518 1847.36  5523.5 1848.43    5533 1849.26  5555.2 1849.75
  5614.5  1853.5  5665.8 1856.03  5733.8 1858.01  5743.3 1857.65  5756.5 1858.56
  5765.4 1858.65  5773.7  1857.9  5779.3 1858.16  5787.5 1857.61  5839.3 1858.25
#Mann= 3 ,-1 , 0
  4636.8     .05       0  4997.8     .05       0  5004.2     .05       0
Bank Sta=4997.8,5004.2
XS Rating Curve= 0 ,0
Exp/Cntr=0.3,0.1

Type RM Length L Ch R = 1 ,46246   ,86,86,86
BEGIN DESCRIPTION:
Mapping XS f688bc11
END DESCRIPTION:
XS GIS Cut Line= 6
      1575689.84      6808815.57      1576116.93      6808755.67
      1576215.89      6808760.88      1576301.82      6808745.26
      1576325.26      6808693.17      1576890.31      6808273.28
#Sta/Elev= 30
  4510.4 1849.83  4748.9 1848.25  4929.6 1843.98  4941.7 1844.29  4949.7  1846.6
  4959.8 1846.78  5029.9 1837.44  5080.1 1835.61  5085.2 1834.32  5097.6 1834.22
  5098.1 1833.72  5103.5 1833.72    5104 1834.22  5121.2 1834.34  5127.2 1834.87
  5136.1 1834.35  5150.3  1835.8  5179.8 1841.31  5185.2 1841.31  5196.7 1843.42
  5202.9 1842.07  5217.5 1842.93    5253 1842.77  5432.4 1845.42  5503.3 1848.04
  5624.3 1854.01  5653.5 1854.16    5689 1855.62  5718.2 1855.31  5889.2 1857.97
#Mann= 3 ,-1 , 0
  4510.4     .05       0  5097.6     .05       0    5104     .05       0
Bank Sta=5097.6,5104
XS Rating Curve= 0 ,0
Exp/Cntr=0.3,0.1

Type RM Length L Ch R = 1 ,46160   ,107,107,107
BEGIN DESCRIPTION:
Mapping XS b49078f2
END DESCRIPTION:
XS GIS Cut Line= 6
      1575710.65      6808859.84      1576153.39      6808807.76
       1576226.3      6808846.82      1576327.87       6808833.8
      1576369.53      6808724.42      1576871.06      6808360.62
#Sta/Elev= 30
  4496.2 1849.77    4712 1848.66  4923.5 1843.69  4945.7 1844.62  4951.3 1846.28
  5017.1 1845.93  5043.6 1847.12  5104.1 1846.14  5123.1 1844.94    5136 1845.43
  5143.7 1843.99  5149.9 1845.48  5158.3 1843.89  5164.5  1845.5  5223.7 1844.45
  5243.7 1844.82    5265  1846.5  5273.5 1843.76  5291.2 1842.54  5291.7 1842.04
  5297.6 1842.54  5409.6 1843.44  5480.7 1845.25  5602.1 1850.18    5667 1851.63
  5696.4 1854.43    5732 1854.81  5752.8 1856.48  5773.7 1855.36  5876.9 1856.55
#Mann= 3 ,-1 , 0
  4496.2     .05       0  5291.2     .05       0  5297.6     .05       0
Bank Sta=5291.2,5297.6
XS Rating Curve= 0 ,0
Exp/Cntr=0.3,0.1

Type RM Length L Ch R = 1 ,46053   ,776,776,776
BEGIN DESCRIPTION:
Mapping XS 9edd31ec
END DESCRIPTION:
XS GIS Cut Line= 4
      1575848.69      6809180.16      1576114.32      6808977.03
      1576559.64      6808807.76      1577064.86      6808453.58
#Sta/Elev= 30
  4526.8 1848.46  4761.3 1847.66    4900 1845.71  4936.8 1842.69  4947.5  1841.3
  4954.9 1839.31  4957.1 1839.22  4957.6 1838.72    4963 1838.72  4963.5 1839.22
    4985 1841.43  5094.8 1842.29  5279.2 1841.21    5342 1841.18  5392.5 1841.83
  5455.3 1843.37  5470.1 1844.64  5484.9 1844.17  5520.7 1845.58  5550.3 1845.61
  5577.3 1846.63  5657.5 1848.09  5686.1 1849.51  5714.2 1851.97  5764.7 1852.96
  5808.2 1855.03  5821.4 1854.87  5886.8 1857.55  5922.5 1856.71  5954.6 1857.11
#Mann= 3 ,-1 , 0
  4526.8     .05       0  4957.1     .05       0  4963.5     .05       0
Bank Sta=4957.1,4963.5
XS Rating Curve= 0 ,0
Exp/Cntr=0.3,0.1

Type RM Length L Ch R = 1 ,45277   ,277,277,277
BEGIN DESCRIPTION:
Mapping XS b91af0a6
END DESCRIPTION:
XS GIS Cut Line= 3
      1575986.71      6809253.07      1576611.72      6809112.44
      1577085.66      6808734.85
#Sta/Elev= 30
  4132.9 1847.51  4418.1 1845.51  4544.7 1843.46  4612.9    1843  4715.4 1841.03
  4746.1 1841.58  4773.5 1843.54  4786.4 1843.91  4792.8 1843.34  4800.8 1843.56
  4807.2 1842.76    4836 1842.06  4842.4 1841.08  4856.9 1840.32    4985 1839.99
  5007.4  1838.2  5017.4 1837.95  5017.9 1837.45  5023.4 1837.45  5023.9 1837.95
  5034.6 1840.07  5057.1 1841.97  5113.1 1844.06  5199.6 1848.27  5220.4 1850.58
  5298.9 1851.29  5313.3 1851.76  5319.7 1853.09  5334.1 1854.07  5379.5 1855.05
#Mann= 3 ,-1 , 0
  4132.9     .05       0  5017.4     .05       0  5023.9     .05       0
Bank Sta=5017.4,5023.9
XS Rating Curve= 0 ,0
Exp/Cntr=0.3,0.1

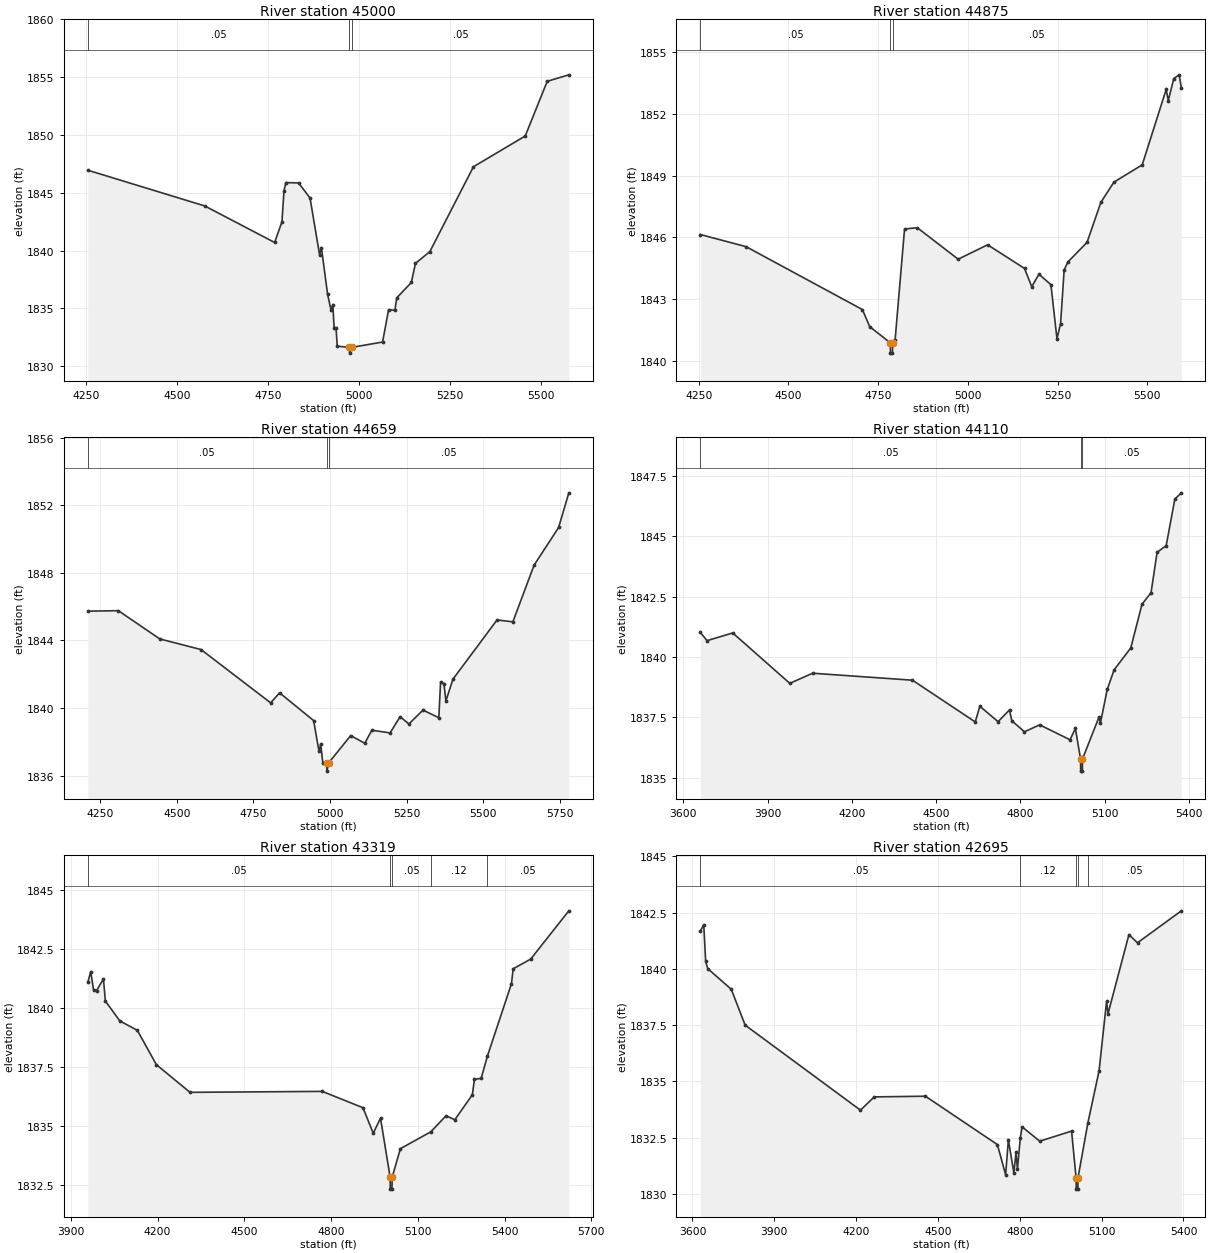
Type RM Length L Ch R = 1 ,45000   ,125,125,125
BEGIN DESCRIPTION:
Mapping XS 902eb1c3
END DESCRIPTION:
XS GIS Cut Line= 6
      1576127.35      6809297.34      1576687.24       6809208.8
      1576794.01      6809245.26      1576937.24      6809195.78
      1576965.89      6809049.94      1577124.72      6808745.29
#Sta/Elev= 30
    4254 1846.96  4575.6 1843.87    4768 1840.71  4788.2 1842.51  4793.6 1845.14
  4798.7 1845.89  4833.9 1845.86  4865.4 1844.55  4891.5 1839.67  4896.7 1840.27
  4913.6 1836.24  4922.8  1834.9  4928.1 1835.34  4931.6 1833.35  4936.8 1833.35
  4940.3 1831.74  4973.8 1831.64  4974.3 1831.14  4980.3 1831.64    5065  1832.1
  5081.4 1834.88  5098.9 1834.85    5104 1835.92  5144.1 1837.25  5155.4  1838.9
    5195 1839.92    5315 1847.26  5457.5 1849.92    5518 1854.65  5577.4 1855.21
#Mann= 3 ,-1 , 0
    4254     .05       0  4973.8     .05       0  4980.3     .05       0
Bank Sta=4973.8,4980.3
XS Rating Curve= 0 ,0
Exp/Cntr=0.3,0.1

Type RM Length L Ch R = 1 ,44875   ,216,216,216
BEGIN DESCRIPTION:
Mapping XS 087cd54e
END DESCRIPTION:
XS GIS Cut Line= 6
       1576179.4      6809406.72      1576741.93      6809315.57
       1576911.2      6809315.57      1576986.72      6809253.07
      1577007.55      6809026.51      1577150.27      6808803.35
#Sta/Elev= 30
  4254.8 1846.14    4382 1845.55  4706.2 1842.49  4726.5 1841.66    4784 1840.87
  4784.5 1840.37    4790 1840.37  4790.5 1840.87  4797.4 1841.02  4823.7 1846.41
  4859.3 1846.47  4973.1 1844.94  5055.2 1845.64    5158 1844.49  5178.1  1843.6
  5198.2 1844.21  5231.5  1843.7  5248.4 1841.07  5258.4  1841.8  5268.4 1844.41
  5278.5  1844.8  5332.2 1845.76  5370.8 1847.71  5407.2 1848.69  5485.9 1849.53
  5552.7  1853.2  5558.6 1852.66  5573.8 1853.73    5589 1853.91    5595 1853.26
#Mann= 3 ,-1 , 0
  4254.8     .05       0    4784     .05       0  4790.5     .05       0
Bank Sta=4784,4790.5
XS Rating Curve= 0 ,0
Exp/Cntr=0.3,0.1

Type RM Length L Ch R = 1 ,44659   ,549,549,549
BEGIN DESCRIPTION:
Mapping XS 3912211c
END DESCRIPTION:
XS GIS Cut Line= 3
       1576471.1      6810055.14      1576945.05       6809646.3
      1577335.67      6808786.94
#Sta/Elev= 30
  4209.7 1845.73  4309.4 1845.76  4444.3 1844.09  4579.2 1843.46  4806.3 1840.31
  4835.6  1840.9  4946.7 1839.26  4964.2 1837.44  4969.7 1837.87  4976.6 1836.77
  4989.4 1836.77  4989.9 1836.27  4996.2 1836.77  5067.5 1838.37  5113.6 1837.92
  5136.7 1838.69  5196.2 1838.53    5229 1839.49  5257.5 1839.06  5303.7 1839.88
  5355.3 1839.43    5361 1841.52    5372 1841.45  5378.4 1840.42  5401.4 1841.71
  5545.3 1845.21    5597  1845.1  5666.2 1848.45  5746.3 1850.68  5779.6 1852.73
#Mann= 3 ,-1 , 0
  4209.7     .05       0  4989.4     .05       0  4996.2     .05       0
Bank Sta=4989.4,4996.2
XS Rating Curve= 0 ,0
Exp/Cntr=0.3,0.1

Type RM Length L Ch R = 1 ,44110   ,791,791,791
BEGIN DESCRIPTION:
Mapping XS 9adc6d4f
END DESCRIPTION:
XS GIS Cut Line= 3
      1577148.18      6810711.37      1577343.49      6809596.82
      1577557.05      6809057.71
#Sta/Elev= 30
  3661.2 1841.02  3684.9 1840.68  3776.3    1841  3979.3 1838.91  4060.6 1839.33
  4415.9 1839.04  4639.2 1837.31  4655.6 1837.96  4720.5 1837.32  4761.1 1837.81
  4769.3 1837.36  4814.4  1836.9  4868.4 1837.19  4976.5 1836.57  4995.5 1837.04
  5013.9 1835.77  5014.4 1835.27  5020.2 1835.27  5020.7 1835.77  5079.2  1837.5
  5084.6 1837.26  5108.9 1838.66  5133.3 1839.47  5192.7 1840.38  5232.5 1842.19
  5264.7 1842.67  5286.2 1844.34  5318.5 1844.62  5349.4 1846.55  5372.6 1846.81
#Mann= 3 ,-1 , 0
  3661.2     .05       0  5013.9     .05       0  5020.7     .05       0
Bank Sta=5013.9,5020.7
XS Rating Curve= 0 ,0
Exp/Cntr=0.3,0.1

Type RM Length L Ch R = 1 ,43319   ,624,624,624
BEGIN DESCRIPTION:
Mapping XS be3e711d
END DESCRIPTION:
XS GIS Cut Line= 3
       1577471.1      6810807.73      1577627.35      6809872.86
      1577876.95      6809202.03
#Sta/Elev= 30
  3958.7 1841.08  3968.6 1841.53  3978.7 1840.74  3988.8 1840.73  4012.7 1841.22
  4019.3 1840.29  4069.1 1839.45  4129.9 1839.05  4195.7  1837.6  4312.1 1836.43
  4769.5 1836.47  4910.3 1835.78  4945.9  1834.7    4971 1835.34  5004.3 1832.84
  5004.8 1832.34  5010.7 1832.34  5011.2 1832.84  5039.8 1834.05  5144.7 1834.76
  5197.7 1835.44    5228 1835.27  5288.7 1836.33  5295.8 1836.98  5319.1 1837.02
  5340.7 1837.96  5423.9 1841.02  5429.8 1841.65  5490.4 1842.06  5622.3  1844.1
#Mann= 5 ,-1 , 0
  3958.7     .05       0  5004.3     .05       0  5011.2     .05       0
  5144.7     .12       0  5340.7     .05       0
Bank Sta=5004.3,5011.2
XS Rating Curve= 0 ,0
Exp/Cntr=0.3,0.1

Type RM Length L Ch R = 1 ,42695   ,601,601,601
BEGIN DESCRIPTION:
Mapping XS f66287aa
END DESCRIPTION:
XS GIS Cut Line= 3
       1577593.5      6810773.88      1578171.62      6809948.38
      1578262.76       6809198.4
#Sta/Elev= 30
    3629 1841.68  3641.3 1841.96  3648.4 1840.33  3656.1 1840.01  3742.4 1839.09
    3793  1837.5  4215.8 1833.72  4266.4 1834.31  4453.9 1834.34  4717.8 1832.19
    4748 1830.85  4758.1  1832.4  4778.2 1830.94  4786.2 1831.85  4791.3  1831.1
  4801.8 1832.49  4808.4 1832.98    4873 1832.34  4989.8 1832.79  5006.4 1830.71
  5006.9 1830.21  5012.9 1830.21  5013.4 1830.71  5049.3 1833.14  5090.5 1835.46
  5118.2 1838.56  5123.3    1838    5200 1841.52  5231.5 1841.16  5392.3 1842.58
#Mann= 5 ,-1 , 0
    3629     .05       0  4801.8     .12       0  5006.4     .07       0
  5013.4     .12       0  5049.3     .05       0
Bank Sta=5006.4,5013.4
XS Rating Curve= 0 ,0
Exp/Cntr=0.3,0.1

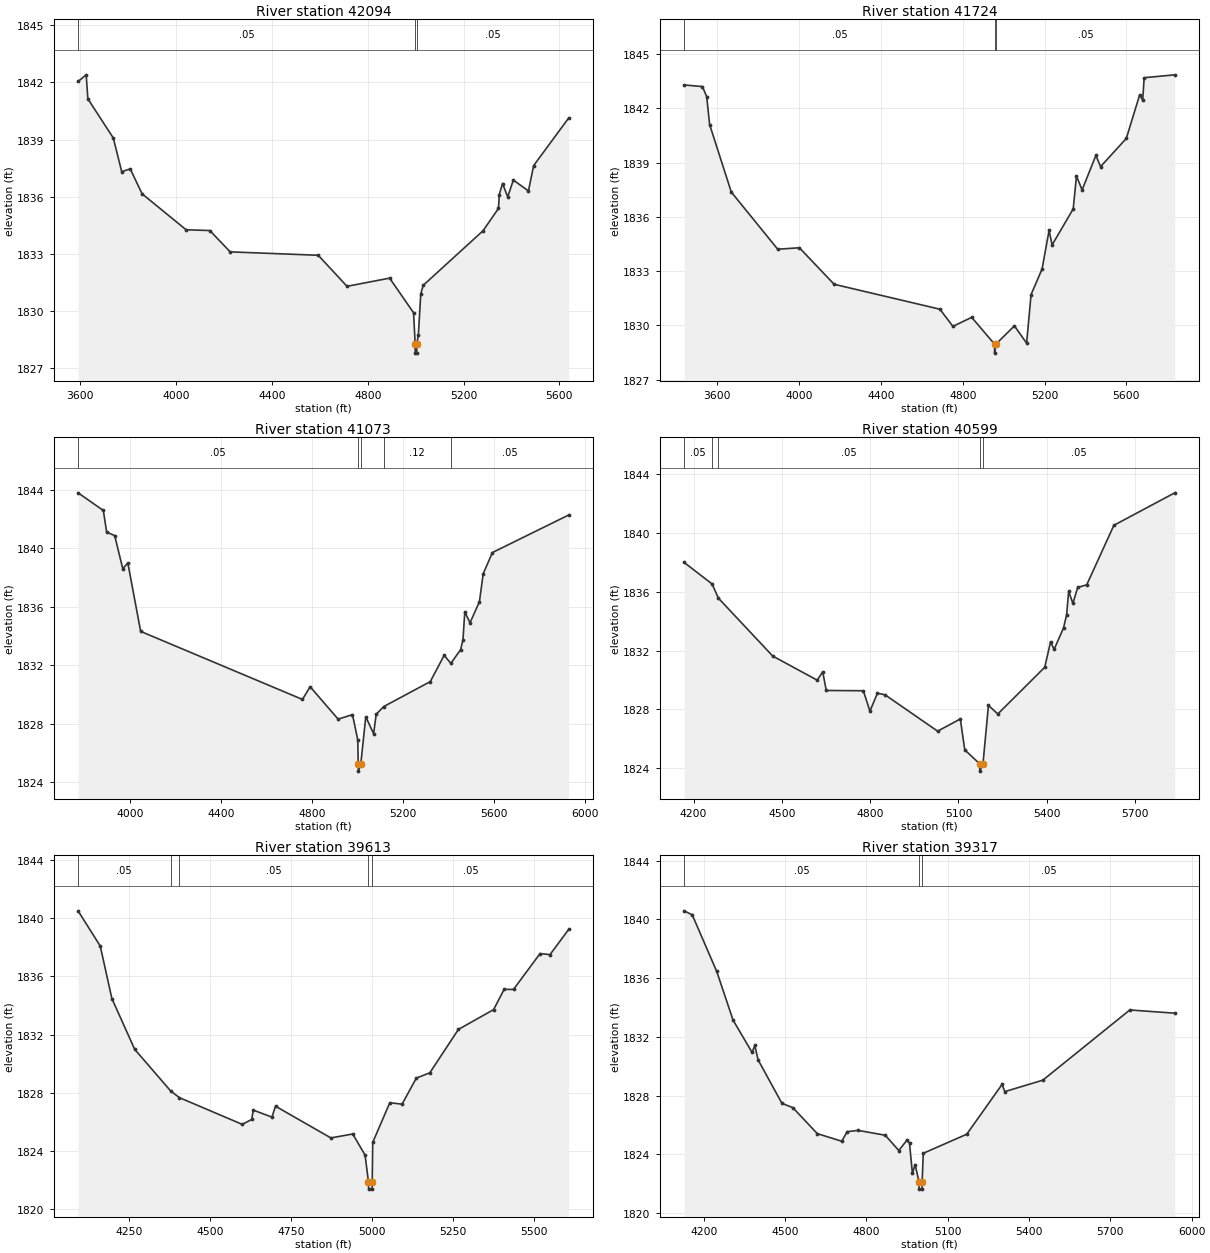
Type RM Length L Ch R = 1 ,42094   ,370,370,370
BEGIN DESCRIPTION:
Mapping XS 4ab247f1
END DESCRIPTION:
XS GIS Cut Line= 4
        1577656.      6810786.91      1578512.76      6809953.59
      1578502.35      6809393.69      1578390.38       6809122.9
#Sta/Elev= 30
  3590.4 1842.05  3624.3  1842.4  3631.3 1841.14  3737.5 1839.08  3772.7 1837.31
  3808.2 1837.46  3857.6 1836.15  4041.5 1834.26  4140.5 1834.22  4225.4  1833.1
  4593.2 1832.92  4713.3 1831.29  4891.2 1831.72  4991.2  1829.9  4997.7 1828.28
  4998.2 1827.78  5004.2 1827.78  5004.7 1828.28  5011.2 1828.73  5021.2 1830.89
  5031.2 1831.34  5281.3 1834.21  5345.6 1835.38    5349 1836.11  5362.6 1836.69
  5384.2 1835.99  5407.7 1836.87  5470.8  1836.3  5492.4 1837.63  5638.6 1840.13
#Mann= 3 ,-1 , 0
  3590.4     .05       0  4997.7     .05       0  5004.7     .05       0
Bank Sta=4997.7,5004.7
XS Rating Curve= 0 ,0
Exp/Cntr=0.3,0.1

Type RM Length L Ch R = 1 ,41724   ,651,651,651
BEGIN DESCRIPTION:
Buttonwillow Creek 41302.081
END DESCRIPTION:
XS GIS Cut Line= 3
      1577708.11      6810846.78      1578805.09      6809827.92
      1579591.94      6809391.14
#Sta/Elev= 30
    3439  1843.3  3528.1 1843.21  3549.1 1842.65  3563.3 1841.11  3669.3 1837.37
    3896 1834.21    4002 1834.29  4171.7 1832.27  4688.6 1830.89  4752.1 1829.94
  4843.9 1830.44  4955.4 1828.96  4955.9 1828.46  4962.4 1828.96  5052.7 1829.97
  5112.2 1829.01    5134  1831.7  5187.7 1833.11    5222 1835.25  5236.9 1834.45
  5339.9 1836.44  5355.9 1838.26  5383.4 1837.49  5450.7  1839.4  5473.6 1838.78
  5599.4 1840.34  5664.9 1842.76  5679.5 1842.45  5686.6  1843.7  5836.1 1843.86
#Mann= 3 ,-1 , 0
    3439     .05       0  4955.4     .05       0  4962.4     .05       0
Bank Sta=4955.4,4962.4
XS Rating Curve= 0 ,0
Exp/Cntr=0.3,0.1

Type RM Length L Ch R = 1 ,41073   ,474,474,474
BEGIN DESCRIPTION:
Mapping XS e7d4de0b
END DESCRIPTION:
XS GIS Cut Line= 3
      1577942.47      6810961.38      1578325.26      6810464.01
      1579804.45      6810078.58
#Sta/Elev= 30
  3772.7 1843.81  3883.8  1842.6  3898.3 1841.12  3933.7 1840.88    3969 1838.62
  3991.5    1839  4047.8 1834.32  4758.9 1829.66  4792.7 1830.53  4915.7 1828.31
  4978.8 1828.62  5001.9  1826.9  5004.2 1825.25  5004.7 1824.75  5015.4 1825.25
  5037.2 1828.47  5071.8 1827.31  5082.9 1828.64  5115.9 1829.17  5320.7 1830.88
  5381.8 1832.68  5411.2 1832.13  5454.1 1833.07  5464.4 1833.74  5472.4 1835.66
  5495.4 1834.91  5536.8 1836.35  5553.4 1838.27  5593.9 1839.72  5928.9 1842.29
#Mann= 5 ,-1 , 0
  3772.7     .05       0  5004.2     .05       0  5015.4     .05       0
  5115.9     .12       0  5411.2     .05       0
Bank Sta=5004.2,5015.4
XS Rating Curve= 0 ,0
Exp/Cntr=0.3,0.1

Type RM Length L Ch R = 1 ,40599   ,986,986,986
BEGIN DESCRIPTION:
Mapping XS f4f44848
END DESCRIPTION:
XS GIS Cut Line= 3
      1578137.76      6811032.58      1578500.17      6810858.97
      1579690.79      6810431.74
#Sta/Elev= 30
    4168    1838  4262.7 1836.54  4284.3 1835.57  4468.9 1831.63    4620 1829.99
  4638.7 1830.56  4650.7 1829.29  4776.8 1829.27  4799.1 1827.88  4824.5  1829.1
    4850    1829  5029.1 1826.52  5106.2 1827.35  5121.3 1825.25  5171.8  1824.3
  5172.3  1823.8  5183.2  1824.3  5201.8 1828.27  5233.6 1827.69  5393.1 1830.87
  5412.8  1832.6  5424.9 1832.09  5456.8 1833.54  5467.4 1834.44  5474.3 1836.03
  5488.7 1835.22    5505  1836.3  5535.7 1836.48    5628 1840.53  5834.8 1842.74
#Mann= 5 ,-1 , 0
    4168     .05       0  4262.7     .12       0  4284.3     .05       0
  5171.8     .05       0  5183.2     .05       0
Bank Sta=5171.8,5183.2
XS Rating Curve= 0 ,0
Exp/Cntr=0.3,0.1

Type RM Length L Ch R = 1 ,39613   ,296,296,296
BEGIN DESCRIPTION:
Mapping XS 57d0cc53
END DESCRIPTION:
XS GIS Cut Line= 3
      1578361.29      6811410.18      1578951.56      6811347.25
      1579797.87      6810987.03
#Sta/Elev= 30
  4092.2 1840.51  4160.6 1838.09  4196.5 1834.48  4266.9 1830.99  4377.4 1828.14
  4404.7 1827.67  4598.8 1825.83  4627.8 1826.17  4632.8 1826.81  4690.4 1826.33
  4701.3 1827.08  4872.1  1824.9  4939.5 1825.17  4977.6 1823.72  4988.1 1821.88
  4988.6 1821.38  4999.2 1821.38  4999.7 1821.88  5001.2 1824.59  5053.9 1827.32
  5091.7 1827.22  5135.7 1829.01  5177.5 1829.38  5265.6 1832.36  5374.2 1833.72
  5406.5 1835.11  5435.6 1835.11  5517.4 1837.57  5548.1  1837.5  5605.6 1839.23
#Mann= 5 ,-1 , 0
  4092.2     .05       0  4377.4     .12       0  4404.7     .05       0
  4988.1     .05       0  4999.7     .05       0
Bank Sta=4988.1,4999.7
XS Rating Curve= 0 ,0
Exp/Cntr=0.3,0.1

Type RM Length L Ch R = 1 ,39317   ,445,445,445
BEGIN DESCRIPTION:
Mapping XS cb556a06
END DESCRIPTION:
XS GIS Cut Line= 2
       1578335.2       6811562.1      1580140.37      6811434.09
#Sta/Elev= 30
    4128 1840.59  4157.9 1840.31  4248.1 1836.46  4308.3 1833.15  4378.4 1830.95
  4388.5 1831.42  4400.7 1830.44  4488.7 1827.48  4528.8 1827.19    4619 1825.42
  4709.3  1824.9  4729.3 1825.55  4769.4 1825.64  4869.7 1825.31  4919.8 1824.27
  4949.9 1824.98  4959.2 1824.78  4969.9 1822.71  4979.9 1823.31  4994.2 1822.14
  4994.7 1821.64  5005.3 1821.64  5005.8 1822.14    5010 1824.08  5170.4 1825.38
  5300.7 1828.77  5310.8 1828.28  5451.1 1829.06  5771.9 1833.84  5937.7 1833.62
#Mann= 3 ,-1 , 0
    4128     .05       0  4994.2     .05       0  5005.8     .05       0
Bank Sta=4994.2,5005.8
XS Rating Curve= 0 ,0
Exp/Cntr=0.3,0.1

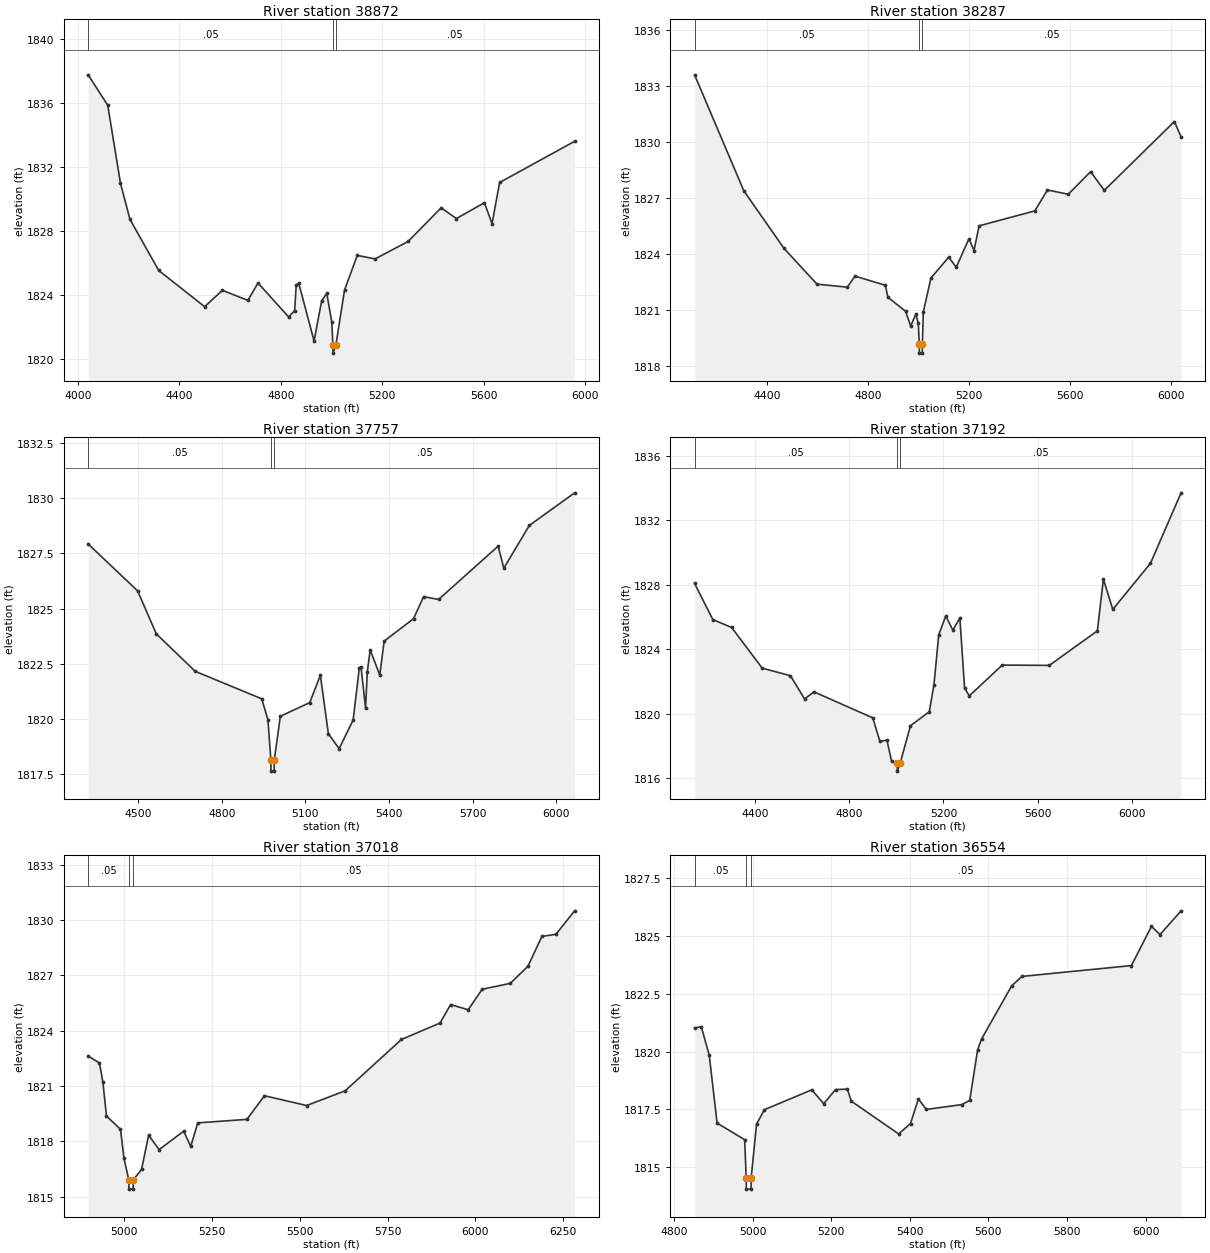
Type RM Length L Ch R = 1 ,38872   ,585,585,585
BEGIN DESCRIPTION:
Mapping XS 25484ac3
END DESCRIPTION:
XS GIS Cut Line= 3
      1578498.03       6811939.7      1579146.88       6811874.6
      1580409.88      6811783.45
#Sta/Elev= 30
  4040.6 1837.75    4118 1835.85  4168.2 1830.98  4205.6 1828.73    4319 1825.54
  4499.9 1823.28  4570.2  1824.3  4670.7 1823.67  4710.4 1824.76  4831.2 1822.64
    4855 1823.03  4861.3 1824.64  4871.3 1824.74  4931.5 1821.14  4961.5 1823.64
  4981.6 1824.11  5001.6  1822.3  5005.8 1820.88  5006.3 1820.38  5017.5 1820.88
  5051.8 1824.32  5101.9 1826.48  5172.1 1826.26  5302.4 1827.35  5432.8 1829.45
  5492.9 1828.78  5603.2 1829.77  5633.3 1828.46  5663.3 1831.03    5959  1833.6
#Mann= 3 ,-1 , 0
  4040.6     .05       0  5005.8     .05       0  5017.5     .05       0
Bank Sta=5005.8,5017.5
XS Rating Curve= 0 ,0
Exp/Cntr=0.3,0.1

Type RM Length L Ch R = 1 ,38287   ,530,530,530
BEGIN DESCRIPTION:
Mapping XS 68bf33f1
END DESCRIPTION:
XS GIS Cut Line= 3
      1578521.85      6812410.62       1579973.7      6812276.07
      1580399.07      6812074.24
#Sta/Elev= 30
  4112.8  1833.6  4307.8  1827.4  4467.5 1824.31    4598  1822.4  4718.5 1822.24
  4748.7 1822.83  4869.2 1822.34  4879.2  1821.7  4949.2 1820.95  4969.6 1820.16
  4989.7 1820.79  4999.7 1820.33  5003.7 1819.21  5004.2 1818.71  5015.4 1818.71
  5015.9 1819.21  5019.8 1820.92  5049.9 1822.73  5120.2 1823.84  5150.4 1823.31
  5200.6 1824.83  5220.7  1824.2  5240.8 1825.52  5461.7 1826.32  5511.9 1827.44
  5594.4 1827.21    5683 1828.42  5737.1 1827.42  6015.1  1831.1  6041.7 1830.28
#Mann= 3 ,-1 , 0
  4112.8     .05       0  5003.7     .05       0  5015.9     .05       0
Bank Sta=5003.7,5015.9
XS Rating Curve= 0 ,0
Exp/Cntr=0.3,0.1

Type RM Length L Ch R = 1 ,37757   ,565,565,565
BEGIN DESCRIPTION:
Mapping XS 1a5dbd9e
END DESCRIPTION:
XS GIS Cut Line= 4
       1578716.3      6813021.74       1579018.4      6812954.02
      1579843.06      6812533.88      1580344.76      6812440.14
#Sta/Elev= 30
  4320.7 1827.93  4498.3  1825.8  4565.3 1823.85    4705 1822.15  4943.6  1820.9
  4965.9 1819.95  4976.4 1818.12  4976.9 1817.62  4988.1 1817.62  4988.6 1818.12
  5010.4 1820.11  5115.9 1820.73    5154 1821.97  5182.6 1819.32  5221.3 1818.64
  5271.6 1819.94  5293.8 1822.32  5299.9 1822.35  5316.1 1820.47  5322.3 1822.12
  5332.7 1823.12  5367.2 1821.98  5382.8 1823.52  5488.4 1824.54  5524.3 1825.54
  5578.1 1825.41  5791.8 1827.83  5812.1 1826.83  5903.7 1828.77  6066.2 1830.25
#Mann= 3 ,-1 , 0
  4320.7     .05       0  4976.4     .05       0  4988.6     .05       0
Bank Sta=4976.4,4988.6
XS Rating Curve= 0 ,0
Exp/Cntr=0.3,0.1

Type RM Length L Ch R = 1 ,37192   ,174,174,174
BEGIN DESCRIPTION:
Mapping XS ce353894
END DESCRIPTION:
XS GIS Cut Line= 3
      1578797.57       6813272.6      1579649.13      6813236.14
      1580865.29      6813189.26
#Sta/Elev= 30
  4141.3 1828.08  4218.8 1825.84  4298.9 1825.35    4429 1822.83  4549.1 1822.36
  4609.2 1820.92  4649.2 1821.36  4899.4 1819.75  4929.4 1818.29  4959.5 1818.37
  4979.5 1817.05  5003.1 1816.95  5003.6 1816.45  5015.9 1816.95  5059.6 1819.26
  5139.6 1820.13  5159.6  1821.8  5179.6 1824.88  5209.7 1826.06  5239.7 1825.19
  5269.7 1825.93  5289.7 1821.61  5309.7 1821.11  5449.8 1823.02    5650    1823
  5854.6 1825.14  5880.2 1828.34  5920.2 1826.47  6080.3 1829.32  6210.7 1833.69
#Mann= 3 ,-1 , 0
  4141.3     .05       0  5003.1     .03       0  5015.9     .05       0
Bank Sta=5003.1,5015.9
XS Rating Curve= 0 ,0
Exp/Cntr=0.3,0.1

Type RM Length L Ch R = 1 ,37018   ,464,464,464
BEGIN DESCRIPTION:
Mapping XS b7a6df01
END DESCRIPTION:
XS GIS Cut Line= 2
      1579552.81      6813410.62      1580938.15       6813397.6
#Sta/Elev= 30
  4897.4 1822.62  4929.6 1822.25  4939.6 1821.19  4949.6 1819.37  4989.6 1818.65
  4999.6 1817.07  5013.2 1815.91  5013.7 1815.41  5025.5 1815.41    5026 1815.91
  5049.6 1816.48  5069.6 1818.33  5099.6 1817.55  5169.6 1818.55  5189.6 1817.72
  5209.6    1819  5349.6 1819.19  5399.6 1820.47  5519.6 1819.94  5629.6 1820.74
  5789.6 1823.52  5899.6 1824.41  5929.6 1825.41  5979.6 1825.13  6019.6 1826.24
  6099.6 1826.56  6149.6 1827.48  6189.6  1829.1  6229.6 1829.22  6282.8 1830.49
#Mann= 3 ,-1 , 0
  4897.4     .05       0  5013.2     .03       0    5026     .05       0
Bank Sta=5013.2,5026
XS Rating Curve= 0 ,0
Exp/Cntr=0.3,0.1

Type RM Length L Ch R = 1 ,36554   ,418,418,418
BEGIN DESCRIPTION:
Mapping XS efaeef73
END DESCRIPTION:
XS GIS Cut Line= 3
      1579557.98      6813871.56      1580362.67      6813798.64
      1580776.73      6813684.06
#Sta/Elev= 30
  4852.6 1821.03  4869.7 1821.08  4889.8 1819.86  4909.9 1816.91  4980.1 1816.19
  4983.8 1814.55  4984.3 1814.05  4996.1 1814.05  4996.6 1814.55  5010.3 1816.87
  5030.3 1817.49  5150.8 1818.35    5181 1817.75  5211.1 1818.36  5241.2 1818.38
  5251.2 1817.86  5371.7 1816.44  5401.9 1816.89  5421.9 1817.96    5442  1817.5
  5532.4 1817.71  5552.5 1817.89  5572.6 1820.08  5582.6 1820.55  5659.2 1822.85
  5685.3 1823.26  5963.9 1823.73  6014.9 1825.43  6036.5 1825.07  6090.2  1826.1
#Mann= 3 ,-1 , 0
  4852.6     .05       0  4983.8     .05       0  4996.6     .05       0
Bank Sta=4983.8,4996.6
XS Rating Curve= 0 ,0
Exp/Cntr=0.3,0.1

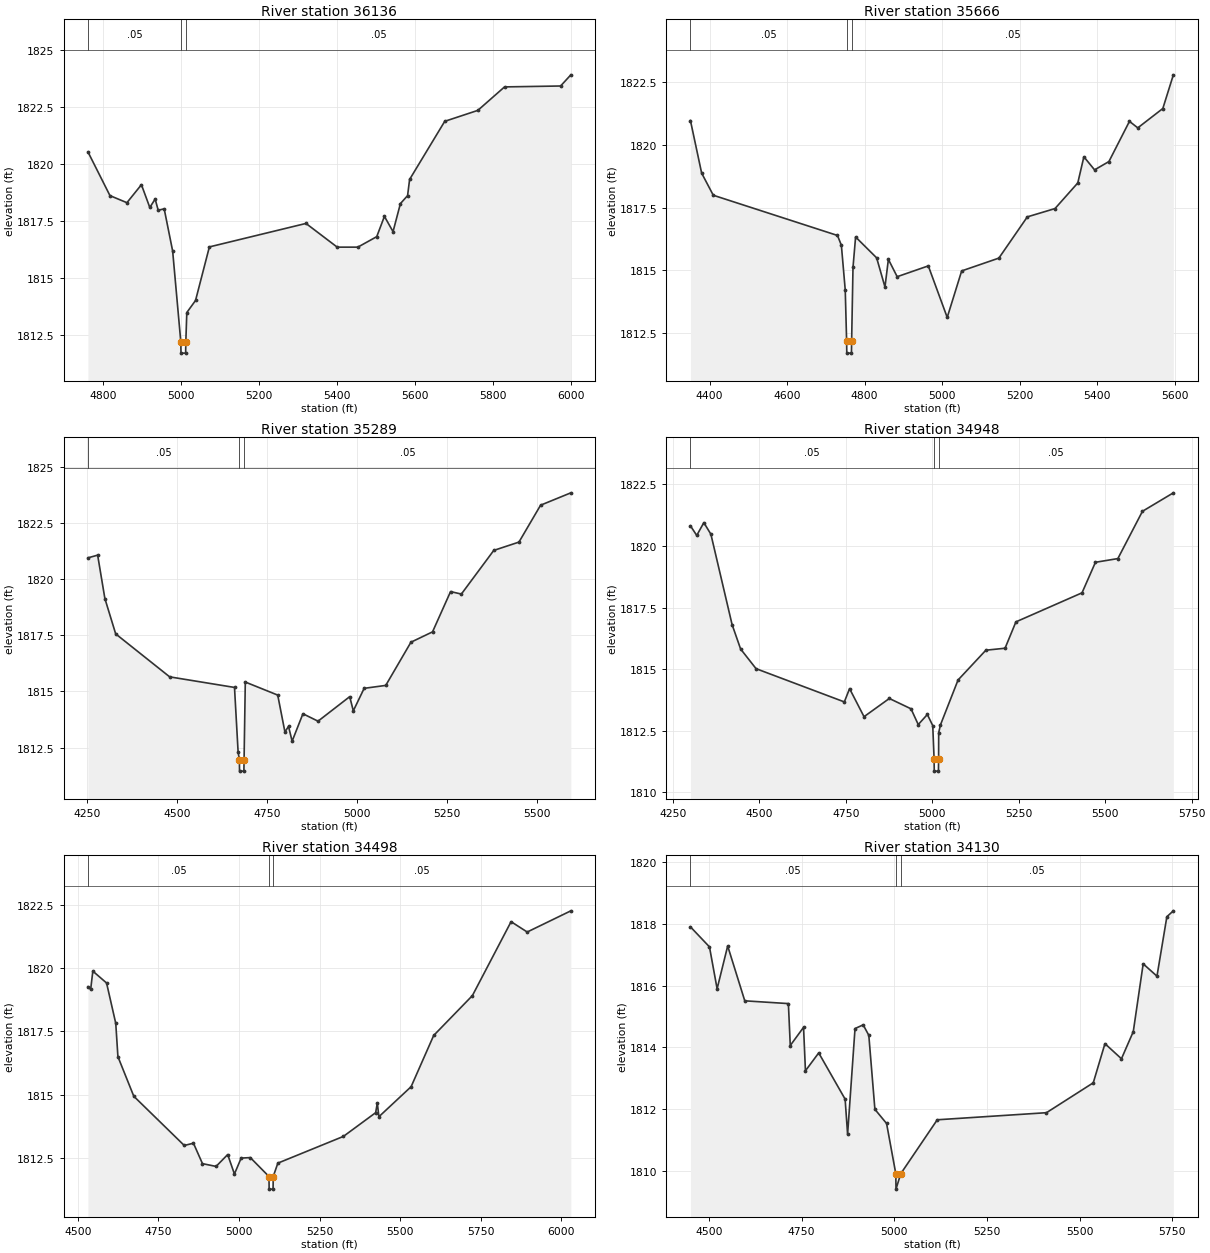
Type RM Length L Ch R = 1 ,36136   ,470,470,470
BEGIN DESCRIPTION:
Mapping XS e0124ce4
END DESCRIPTION:
XS GIS Cut Line= 3
      1579576.24      6814335.08      1580211.63       6813962.7
      1580700.65      6813848.25
#Sta/Elev= 30
  4761.1 1820.53  4817.6 1818.61  4861.1  1818.3  4898.3 1819.09  4919.8 1818.09
  4933.5 1818.46  4941.3 1817.97  4956.7 1818.03  4978.4 1816.18  4999.3  1812.2
  4999.8  1811.7  5011.7  1811.7  5012.2  1812.2  5014.7 1813.48  5037.1 1814.01
  5072.6 1816.36  5320.4 1817.39  5400.5 1816.35  5453.4 1816.35  5501.9 1816.81
  5521.6  1817.7  5543.7 1817.03  5562.6 1818.26    5581 1818.61  5586.2 1819.32
  5676.3 1821.87  5761.2 1822.35  5829.7 1823.38  5973.5 1823.42  5999.8 1823.91
#Mann= 3 ,-1 , 0
  4761.1     .05       0  4999.3     .05       0  5012.2     .05       0
Bank Sta=4999.3,5012.2
XS Rating Curve= 0 ,0
Exp/Cntr=0.3,0.1

Type RM Length L Ch R = 1 ,35666   ,377,377,377
BEGIN DESCRIPTION:
Mapping XS 24aa0504
END DESCRIPTION:
XS GIS Cut Line= 3
      1579576.18      6814512.18       1580003.3      6814488.74
      1580710.83      6814077.75
#Sta/Elev= 30
  4350.5 1820.96  4379.4 1818.87  4409.4 1817.99  4729.9 1816.39  4739.9    1816
  4749.9 1814.22  4753.4 1812.21  4753.9 1811.71  4765.9 1811.71  4766.4 1812.21
  4769.9 1815.12  4776.6 1816.33  4830.9  1815.5  4852.4 1814.34  4861.2 1815.44
  4883.9 1814.75  4964.2 1815.18    5013 1813.13  5050.3 1814.98  5146.3 1815.49
  5219.7 1817.13  5291.1 1817.46  5349.9 1818.48  5365.6 1819.52  5393.2    1819
  5430.2 1819.33  5483.2 1820.93  5504.7 1820.67  5569.3 1821.44  5596.5 1822.78
#Mann= 3 ,-1 , 0
  4350.5     .05       0  4753.4     .05       0  4766.4     .05       0
Bank Sta=4753.4,4766.4
XS Rating Curve= 0 ,0
Exp/Cntr=0.3,0.1

Type RM Length L Ch R = 1 ,35289   ,341,341,341
BEGIN DESCRIPTION:
Mapping XS a7b36c3d
END DESCRIPTION:
XS GIS Cut Line= 2
      1579557.97      6814694.47       1580899.1      6814733.54
#Sta/Elev= 30
  4252.6 1820.94  4279.6 1821.06  4299.7 1819.13  4329.7 1817.56  4479.7 1815.65
  4659.8 1815.18  4669.8 1812.32  4673.3 1811.96  4673.8 1811.46  4685.9 1811.46
  4686.4 1811.96  4689.8 1815.42  4779.9 1814.84  4799.9  1813.2  4809.9 1813.45
  4819.9 1812.79  4849.9 1814.01  4891.9 1813.68  4979.9 1814.77  4989.9 1814.14
    5020 1815.14    5080 1815.27    5150 1817.19    5210 1817.65  5260.1 1819.44
  5290.1 1819.33  5380.1 1821.27  5450.1 1821.64  5510.2 1823.28  5594.3 1823.83
#Mann= 3 ,-1 , 0
  4252.6     .05       0  4673.3     .05       0  4686.4     .05       0
Bank Sta=4673.3,4686.4
XS Rating Curve= 0 ,0
Exp/Cntr=0.3,0.1

Type RM Length L Ch R = 1 ,34948   ,450,450,450
BEGIN DESCRIPTION:
Mapping XS 19d4df84
END DESCRIPTION:
XS GIS Cut Line= 3
      1579537.15      6814853.33      1579883.51      6814926.24
      1580880.48       6815230.8
#Sta/Elev= 30
  4300.7 1820.82  4318.9 1820.43  4339.4 1820.95  4359.8 1820.48  4421.1 1816.81
  4445.7 1815.82  4490.4 1815.02  4745.7 1813.67  4760.8 1814.21  4802.6 1813.07
  4875.8 1813.81  4938.5 1813.39  4959.4 1812.75  4985.7 1813.16  5001.3 1812.71
  5005.2 1811.36  5005.7 1810.86  5017.8 1810.86  5018.3 1811.36  5018.5 1812.42
  5023.7 1812.74  5074.5 1814.56  5154.9 1815.77  5210.4 1815.85  5241.8 1816.92
    5433  1818.1  5471.8 1819.34  5536.6 1819.49  5607.7 1821.41  5697.1 1822.16
#Mann= 3 ,-1 , 0
  4300.7     .05       0  5005.2     .05       0  5018.3     .05       0
Bank Sta=5005.2,5018.3
XS Rating Curve= 0 ,0
Exp/Cntr=0.3,0.1

Type RM Length L Ch R = 1 ,34498   ,368,368,368
BEGIN DESCRIPTION:
Mapping XS f9231e7f
END DESCRIPTION:
XS GIS Cut Line= 3
      1579550.16      6814931.43      1580013.72      6815457.49
      1580810.34      6815439.27
#Sta/Elev= 30
  4531.2 1819.27  4539.7 1819.17  4546.4 1819.89    4589 1819.42  4617.5 1817.82
  4624.2  1816.5  4673.5 1814.93    4830 1812.98  4858.5 1813.07  4886.5 1812.26
  4928.7 1812.15  4964.7 1812.62  4985.6 1811.85  5006.5 1812.48  5034.9  1812.5
  5092.8 1811.75  5093.3 1811.25  5105.5 1811.25    5106 1811.75  5120.3 1812.28
  5323.7 1813.34  5423.7 1814.28  5428.8 1814.66  5433.8 1814.12  5533.7 1815.31
  5603.7 1817.34  5723.8 1818.92  5843.8 1821.85  5893.8 1821.44  6029.2 1822.28
#Mann= 3 ,-1 , 0
  4531.2     .05       0  5092.8     .05       0    5106     .05       0
Bank Sta=5092.8,5106
XS Rating Curve= 0 ,0
Exp/Cntr=0.3,0.1

Type RM Length L Ch R = 1 ,34130   ,573,573,573
BEGIN DESCRIPTION:
Mapping XS 5ae584bc
END DESCRIPTION:
XS GIS Cut Line= 3
      1579125.29      6815427.55      1579483.33      6815518.69
      1580370.45      6815807.17
#Sta/Elev= 30
  4450.4 1817.91  4501.7 1817.26  4522.3  1815.9  4550.8 1817.29  4596.9 1815.51
  4714.5 1815.42  4719.6 1814.06  4755.4 1814.65  4760.5 1813.24  4796.3 1813.82
  4867.5 1812.32  4874.2 1811.18  4894.2 1814.61  4916.2 1814.73  4931.4 1814.39
  4947.8 1811.99  4979.3 1811.53  5004.2  1809.9  5004.7  1809.4  5017.5  1809.9
    5116 1811.65  5410.5 1811.88  5536.7 1812.85  5568.2 1814.12  5612.7 1813.63
  5644.6 1814.51  5671.3 1816.71  5708.5 1816.31  5735.2 1818.24  5752.7 1818.43
#Mann= 3 ,-1 , 0
  4450.4     .05       0  5004.2     .03       0  5017.5     .05       0
Bank Sta=5004.2,5017.5
XS Rating Curve= 0 ,0
Exp/Cntr=0.3,0.1