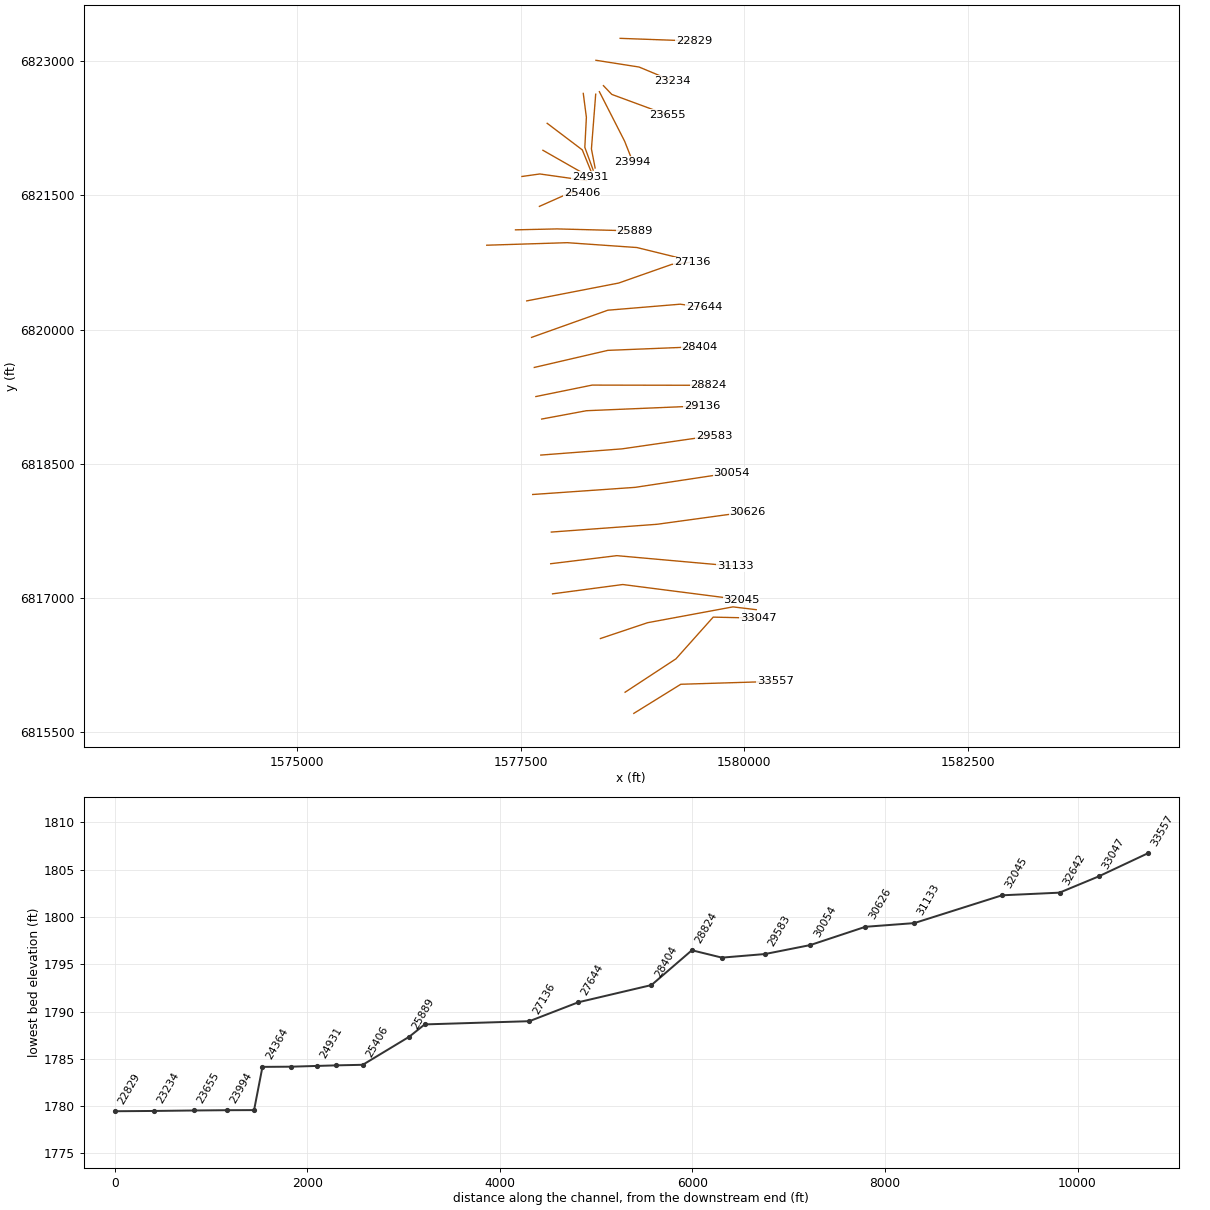
HEC-RAS study Buttonwillow Creek.prj: Buttonwillow Creek Base Level Engineering

--- Buttonwillow Creek.g01 (geometry) --- (continued)

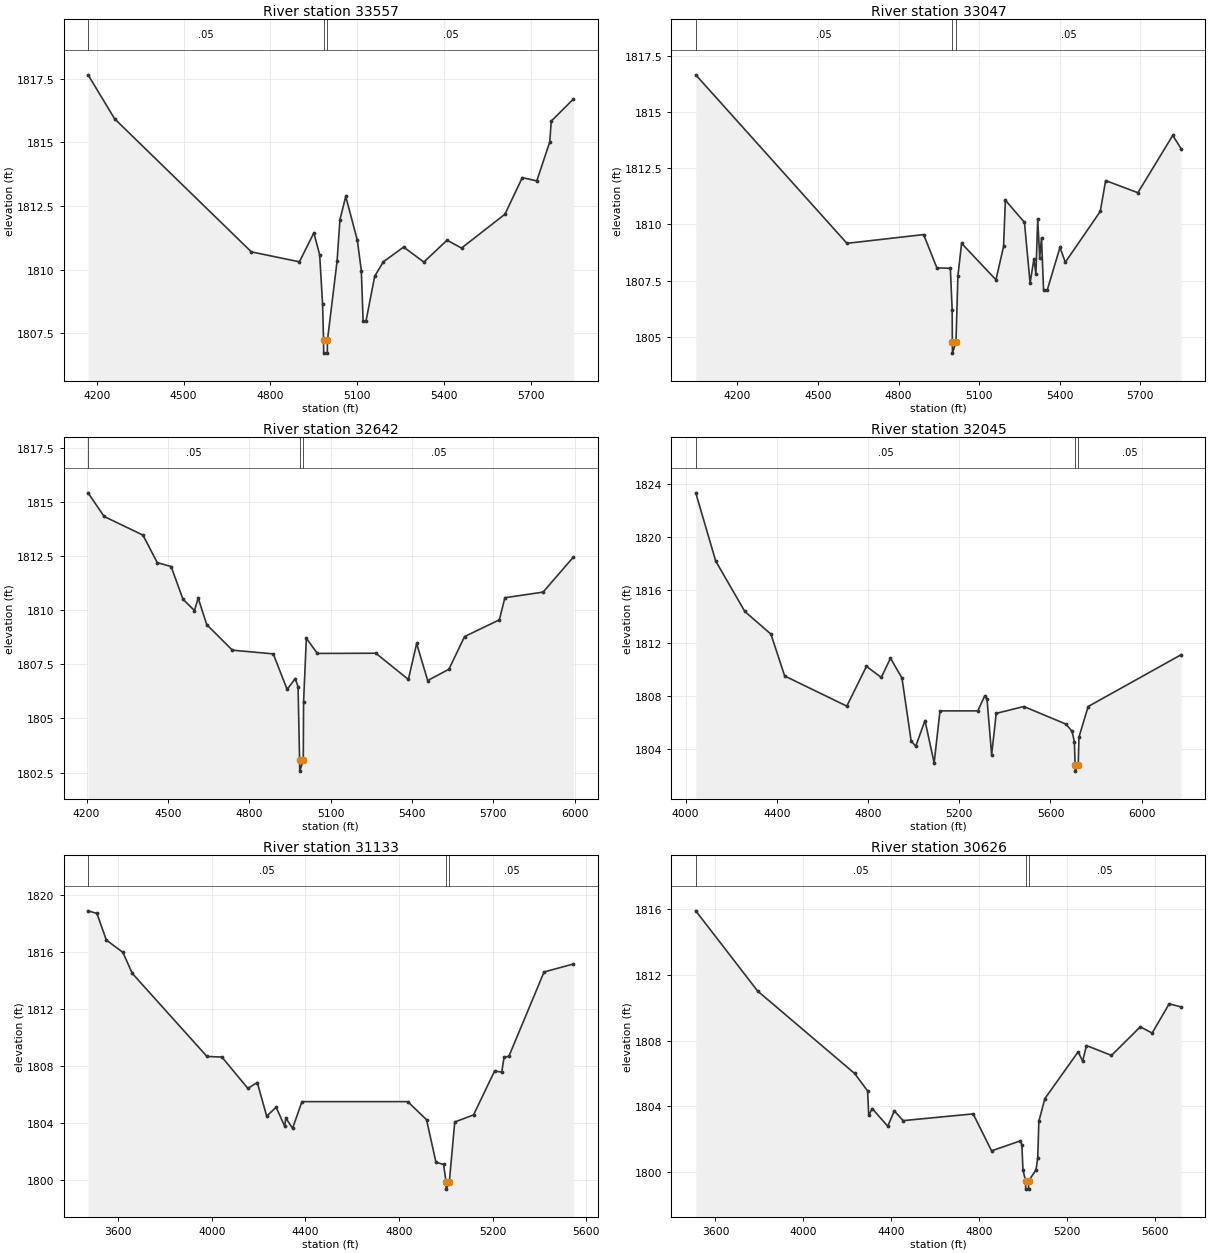
Type RM Length L Ch R = 1 ,33557   ,510,510,510
BEGIN DESCRIPTION:
Mapping XS 6c71eb0e
END DESCRIPTION:
XS GIS Cut Line= 3
      1578767.15      6815707.47      1579292.36      6816033.02
      1580351.74      6816065.51
#Sta/Elev= 30
  4169.9 1817.66  4261.8 1815.93  4734.4  1810.7  4900.5 1810.31  4950.5 1811.45
  4970.5 1810.58  4980.6 1808.64  4983.9 1807.22  4984.4 1806.72  4996.8 1806.72
  4997.3 1807.22  5030.6 1810.33  5040.6 1811.97  5060.6 1812.88  5100.6 1811.16
  5114.5 1809.96  5120.6 1807.99  5130.6 1807.98  5160.6 1809.74  5190.6 1810.31
  5260.7 1810.89  5330.7  1810.3  5410.8 1811.16  5460.8 1810.85  5610.8 1812.18
  5670.9 1813.62  5720.9 1813.49  5765.8 1815.02  5770.9 1815.84  5847.7 1816.71
#Mann= 3 ,-1 , 0
  4169.9     .05       0  4983.9     .05       0  4997.3     .05       0
Bank Sta=4983.9,4997.3
XS Rating Curve= 0 ,0
Exp/Cntr=0.3,0.1

Type RM Length L Ch R = 1 ,33047   ,405,405,405
BEGIN DESCRIPTION:
Mapping XS 8ef426eb
END DESCRIPTION:
XS GIS Cut Line= 4
      1578669.54      6815944.05      1579238.11       6816317.3
      1579654.78      6816783.88      1580156.07      6816773.03
#Sta/Elev= 30
    4045 1816.65  4607.9 1809.16  4893.4 1809.55  4942.7 1808.07  4992.9 1808.05
  4999.6  1806.2  5000.3 1804.78  5000.8 1804.28  5013.8 1804.78    5021 1807.71
  5034.7 1809.16  5162.6 1807.54    5191 1809.02  5197.7 1811.08  5268.8 1810.09
  5289.7 1807.39  5303.9 1808.46  5311.4 1807.81  5318.1 1810.24  5325.6 1808.53
  5332.3  1809.4  5339.8  1807.1  5353.3 1807.07  5400.9 1808.98  5420.9 1808.32
    5551 1810.58    5571 1811.95    5691 1811.41    5821 1813.96  5852.1 1813.36
#Mann= 3 ,-1 , 0
    4045     .05       0  5000.3     .05       0  5013.8     .05       0
Bank Sta=5000.3,5013.8
XS Rating Curve= 0 ,0
Exp/Cntr=0.3,0.1

Type RM Length L Ch R = 1 ,32642   ,597,597,597
BEGIN DESCRIPTION:
Mapping XS 27a31130
END DESCRIPTION:
XS GIS Cut Line= 4
      1578393.07      6816544.45      1578920.83      6816721.53
       1579875.7      6816898.61      1580136.11      6816867.36
#Sta/Elev= 30
  4205.4 1815.41  4264.6 1814.32  4407.8 1813.46  4460.6 1812.19  4511.6 1812.01
  4555.5  1810.5  4597.7 1809.98  4611.5 1810.55  4643.1 1809.33  4737.7 1808.15
  4888.4 1807.98  4939.5 1806.34  4969.7 1806.84  4979.9 1806.46  4985.5 1803.07
    4986 1802.57  4999.1 1803.07  5000.2 1805.76  5010.4  1808.7  5051.1    1808
  5266.7 1808.01  5386.7  1806.8  5417.2 1808.46  5457.9 1806.75  5536.1 1807.27
    5594 1808.78  5722.3 1809.55  5742.6 1810.57  5883.6 1810.83  5995.5 1812.45
#Mann= 3 ,-1 , 0
  4205.4     .05       0  4985.5     .05       0  4999.1     .05       0
Bank Sta=4985.5,4999.1
XS Rating Curve= 0 ,0
Exp/Cntr=0.3,0.1

Type RM Length L Ch R = 1 ,32045   ,912,912,912
BEGIN DESCRIPTION:
Mapping XS 89f57541
END DESCRIPTION:
XS GIS Cut Line= 3
      1577858.31      6817044.44      1578643.06      6817148.61
      1579969.46      6816978.47
#Sta/Elev= 30
  4044.2 1823.35  4131.7 1818.19  4259.5 1814.37  4373.8 1812.66  4434.3 1809.49
  4706.7 1807.21  4792.8 1810.22    4858 1809.38  4898.3 1810.84  4948.7 1809.33
    4989 1804.56  5009.2 1804.18  5049.5 1806.12  5089.8 1802.91  5115.4 1806.85
  5281.4 1806.85  5311.6 1807.99  5321.7 1807.75  5341.9 1803.52  5362.1 1806.66
    5483 1807.18  5667.7 1805.85  5694.8  1805.3  5704.8  1804.5  5708.1 1802.79
  5708.6 1802.29  5721.7 1802.79    5725 1804.87  5765.3 1807.18  6173.1  1811.1
#Mann= 3 ,-1 , 0
  4044.2     .05       0  5708.1     .05       0  5721.7     .05       0
Bank Sta=5708.1,5721.7
XS Rating Curve= 0 ,0
Exp/Cntr=0.3,0.1

Type RM Length L Ch R = 1 ,31133   ,507,507,507
BEGIN DESCRIPTION:
Mapping XS c2be7645
END DESCRIPTION:
XS GIS Cut Line= 3
      1577837.53      6817381.25      1578577.08      6817471.53
      1579899.98      6817353.47
#Sta/Elev= 30
  3471.5 1818.88  3509.2  1818.7  3549.5 1816.83  3620.1 1815.97  3660.4 1814.49
  3979.4 1808.66  4043.2 1808.62    4154 1806.42  4194.3 1806.83  4234.5 1804.47
  4274.7  1805.1  4311.2 1803.77  4316.2 1804.34    4345 1803.62  4385.1 1805.49
  4836.9 1805.49  4917.2 1804.22  4957.4 1801.24    4990 1801.08  5000.7 1799.85
  5001.2 1799.35  5014.5 1799.85  5037.7 1804.06    5118 1804.56  5207.9 1807.64
  5238.5 1807.56  5248.5 1808.63  5268.6 1808.66  5419.2 1814.59  5544.7 1815.15
#Mann= 3 ,-1 , 0
  3471.5     .05       0  5000.7     .05       0  5014.5     .05       0
Bank Sta=5000.7,5014.5
XS Rating Curve= 0 ,0
Exp/Cntr=0.3,0.1

Type RM Length L Ch R = 1 ,30626   ,572,572,572
BEGIN DESCRIPTION:
Mapping XS 67707f6f
END DESCRIPTION:
XS GIS Cut Line= 3
      1577844.45      6817735.42        1579025.      6817822.22
       1580038.9      6817961.11
#Sta/Elev= 30
  3510.3  1815.9  3791.6 1811.02  4232.8    1806  4291.7 1804.94  4296.8 1803.45
    4313 1803.86  4383.2 1802.79  4413.3 1803.72  4453.4 1803.13  4771.6 1803.54
  4855.5 1801.29  4986.7  1801.9  4993.1 1801.67  4998.2 1800.12  5010.1 1799.46
  5010.6 1798.96  5023.4 1798.96  5023.9 1799.46  5057.4 1800.13  5065.3 1800.86
  5070.4 1803.09  5097.8 1804.47  5249.2 1807.32  5269.4 1806.75  5286.9  1807.7
  5400.6  1807.1  5531.8 1808.84  5585.6 1808.46    5663 1810.24  5717.4 1810.05
#Mann= 3 ,-1 , 0
  3510.3     .05       0  5010.1     .05       0  5023.9     .05       0
Bank Sta=5010.1,5023.9
XS Rating Curve= 0 ,0
Exp/Cntr=0.3,0.1

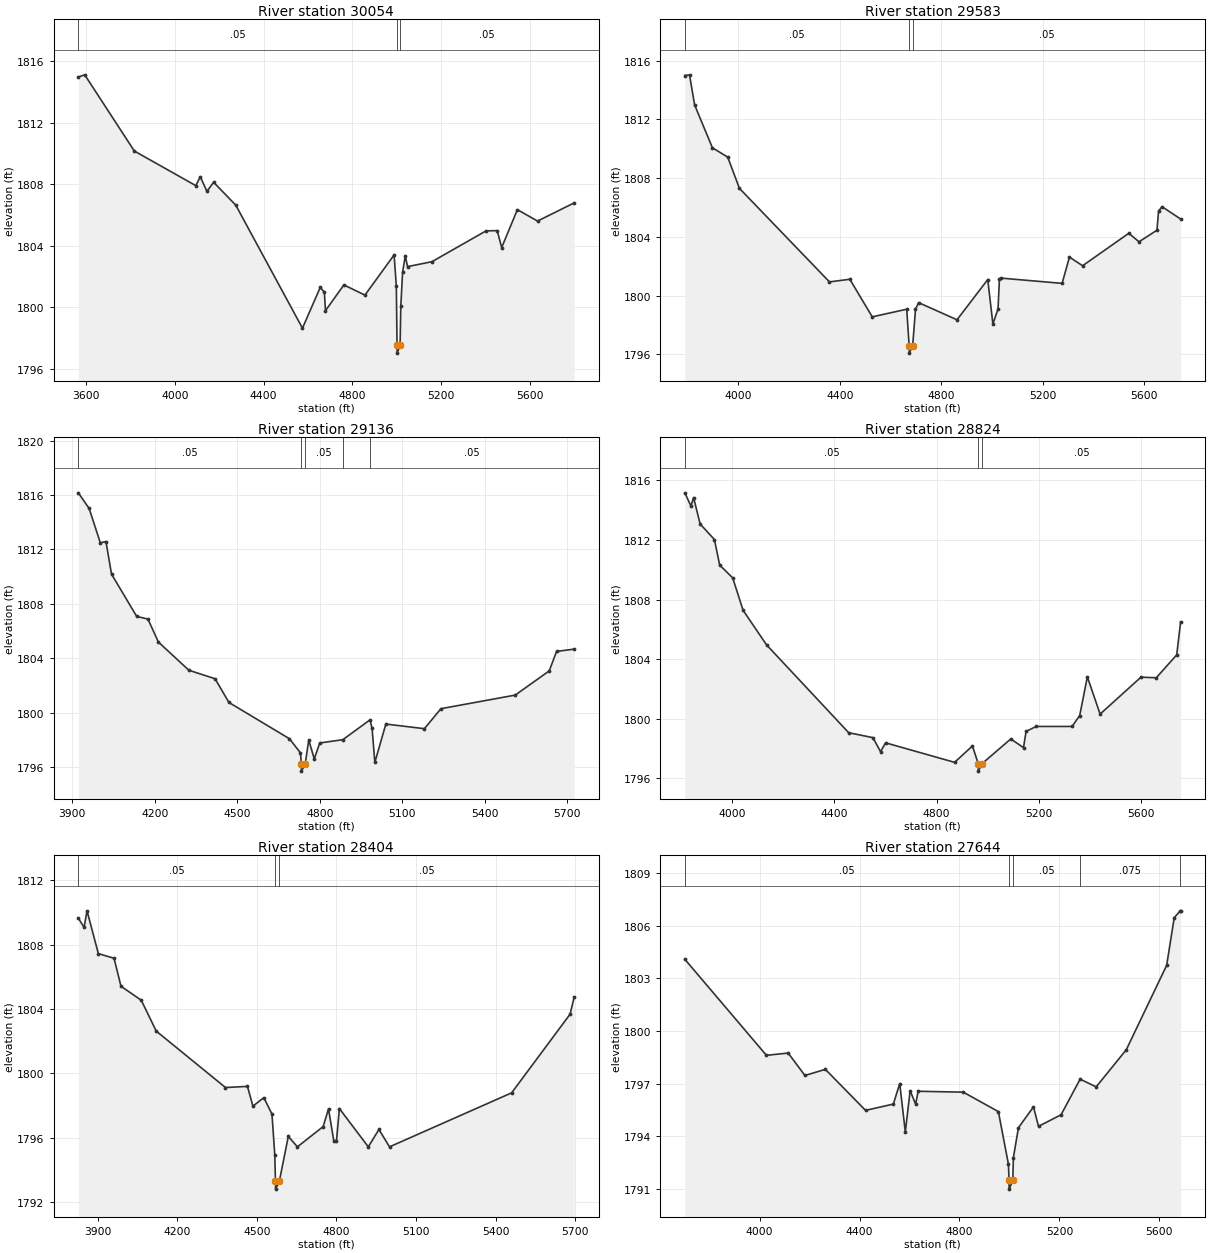
Type RM Length L Ch R = 1 ,30054   ,471,471,471
BEGIN DESCRIPTION:
Mapping XS 60ba8b53
END DESCRIPTION:
XS GIS Cut Line= 3
      1577636.12      6818155.56      1578781.95      6818235.42
      1579858.34      6818398.61
#Sta/Elev= 30
  3563.8 1814.97  3592.7 1815.11  3816.5 1810.16    4094 1807.91    4114 1808.49
  4144.1 1807.54  4174.2 1808.13  4274.4 1806.64  4575.1 1798.65  4655.3  1801.3
    4674 1800.99    4679 1799.79    4762 1801.46  4857.1  1800.8  4988.6 1803.41
  4998.7 1801.38  5001.9 1797.53  5002.4 1797.03  5015.7 1797.53  5018.9 1800.07
  5026.9 1802.28  5039.1 1803.35  5049.3 1802.65  5159.4 1802.97  5403.3 1804.97
  5453.8 1804.99  5474.1 1803.89  5544.9 1806.35  5635.9 1805.61  5801.1 1806.79
#Mann= 3 ,-1 , 0
  3563.8     .05       0  5001.9     .05       0  5015.7     .05       0
Bank Sta=5001.9,5015.7
XS Rating Curve= 0 ,0
Exp/Cntr=0.3,0.1

Type RM Length L Ch R = 1 ,29583   ,447,447,447
BEGIN DESCRIPTION:
Mapping XS 56fe1b57
END DESCRIPTION:
XS GIS Cut Line= 3
      1577726.42      6818596.53      1578636.11      6818665.97
      1579667.32      6818815.27
#Sta/Elev= 30
  3788.4 1814.98    3807 1815.03  3827.1 1812.98  3897.3 1810.06  3957.5 1809.43
  4003.7  1807.3  4358.6 1800.93  4438.9 1801.11  4527.2 1798.55  4663.1 1799.07
  4672.7 1796.58  4673.2 1796.08  4686.5 1796.58  4697.7 1799.06  4709.7 1799.52
  4861.3 1798.35  4982.5 1801.09  5002.7 1798.07    5023 1799.08  5028.5 1801.11
  5033.5 1801.19  5275.6 1800.83  5304.5 1802.62  5356.4 1802.03  5538.3 1804.24
  5578.7 1803.66  5649.4 1804.45  5655.8 1805.76  5669.6 1806.05  5742.7 1805.21
#Mann= 3 ,-1 , 0
  3788.4     .05       0  4672.7     .05       0  4686.5     .05       0
Bank Sta=4672.7,4686.5
XS Rating Curve= 0 ,0
Exp/Cntr=0.3,0.1

Type RM Length L Ch R = 1 ,29136   ,312,312,312
BEGIN DESCRIPTION:
Mapping XS 0c3fb161
END DESCRIPTION:
XS GIS Cut Line= 3
      1577736.33       6818999.3      1578237.67      6819092.62
      1579528.88      6819146.87
#Sta/Elev= 30
  3922.3 1816.16  3961.6 1815.01  4002.3 1812.48  4022.7 1812.58    4043 1810.18
  4134.6 1807.07  4175.2 1806.88  4213.3 1805.19  4323.9 1803.12  4419.4 1802.49
  4469.6 1800.75  4689.8 1798.08  4729.8 1797.04  4732.9  1796.2  4733.4  1795.7
  4746.7  1796.2  4759.9 1797.99  4779.9  1796.6  4799.9 1797.77  4883.6 1798.01
  4982.6 1799.47  4990.1 1798.84  5000.1 1796.34  5040.1 1799.16  5180.2 1798.82
  5240.3 1800.29  5510.5 1801.29    5634 1803.07  5660.7  1804.5  5724.6 1804.67
#Mann= 5 ,-1 , 0
  3922.3     .05       0  4732.9     .05       0  4746.7     .05       0
  4883.6     .12       0  4982.6     .05       0
Bank Sta=4732.9,4746.7
XS Rating Curve= 0 ,0
Exp/Cntr=0.3,0.1

Type RM Length L Ch R = 1 ,28824   ,420,420,420
BEGIN DESCRIPTION:
Mapping XS 1759900f
END DESCRIPTION:
XS GIS Cut Line= 3
      1577671.26      6819251.04      1578300.61      6819379.08
      1579600.26      6819376.91
#Sta/Elev= 30
  3813.9 1815.17  3838.1 1814.28  3848.3 1814.85  3873.9 1813.08    3930 1812.03
  3950.4 1810.32  4001.4 1809.46  4042.2 1807.28  4134.1 1804.96  4455.8 1799.06
  4550.5 1798.73  4580.5 1797.79  4600.5 1798.38  4870.5 1797.07  4940.5 1798.17
  4963.1 1796.98  4963.6 1796.48  4977.9 1796.98  5090.5 1798.64  5140.5 1798.06
  5150.5 1799.15  5190.5 1799.48  5330.5 1799.48  5360.5 1800.21  5390.5 1802.81
  5440.5 1800.31  5600.5 1802.79  5660.5 1802.75  5740.5 1804.29  5755.8 1806.51
#Mann= 3 ,-1 , 0
  3813.9     .05       0  4963.1     .05       0  4977.9     .05       0
Bank Sta=4963.1,4977.9
XS Rating Curve= 0 ,0
Exp/Cntr=0.3,0.1

Type RM Length L Ch R = 1 ,28404   ,760,760,760
BEGIN DESCRIPTION:
Mapping XS aab38d50
END DESCRIPTION:
XS GIS Cut Line= 3
       1577653.9      6819576.56      1578476.39      6819767.54
      1579500.39      6819808.76
#Sta/Elev= 30
  3826.8 1809.65  3848.5 1809.08  3859.6 1810.11  3902.2 1807.45  3961.4 1807.16
  3987.5 1805.42    4064 1804.55  4120.5 1802.63  4381.5 1799.12  4464.4 1799.19
    4485 1797.96    4526 1798.49  4556.8 1797.47  4567.5  1794.9  4569.9  1793.3
  4570.4  1792.8  4584.7  1793.3  4618.4 1796.08  4652.7 1795.43  4749.8 1796.69
  4769.9 1797.79  4789.9  1795.8  4799.9 1795.78    4811 1797.81    4920 1795.43
    4960 1796.51    5000 1795.43  5460.4 1798.79  5680.6 1803.68    5696 1804.74
#Mann= 3 ,-1 , 0
  3826.8     .05       0  4569.9     .05       0  4584.7     .05       0
Bank Sta=4569.9,4584.7
XS Rating Curve= 0 ,0
Exp/Cntr=0.3,0.1

Type RM Length L Ch R = 1 ,27644   ,508,508,508
BEGIN DESCRIPTION:
Mapping XS df1be954
END DESCRIPTION:
XS GIS Cut Line= 4
      1577623.49      6819912.92      1578476.39      6820216.75
      1579285.85      6820284.03      1579550.34      6820247.17
#Sta/Elev= 30
  3700.6 1804.09  4027.3 1798.61  4114.5 1798.74  4181.4 1797.46  4263.3 1797.81
  4424.1 1795.47  4535.4 1795.83  4560.9    1797  4583.3 1794.24  4602.6 1796.59
  4624.7 1795.82  4634.7 1796.56  4815.3 1796.51  4955.8  1795.4    4996 1792.41
  4998.5 1791.48    4999 1790.98  5013.4 1791.48    5016 1792.78  5036.1 1794.48
  5096.3 1795.67  5116.4 1794.56  5206.7 1795.22    5283 1797.25  5347.2 1796.81
  5467.9 1798.93  5629.4 1803.74  5659.7 1806.46  5682.6 1806.83  5685.3 1806.85
#Mann= 5 ,-1 , 0
  3700.6     .05       0  4998.5     .05       0  5013.4     .05       0
    5283    .075       0  5682.6     .05       0
Bank Sta=4998.5,5013.4
XS Rating Curve= 0 ,0
Exp/Cntr=0.3,0.1

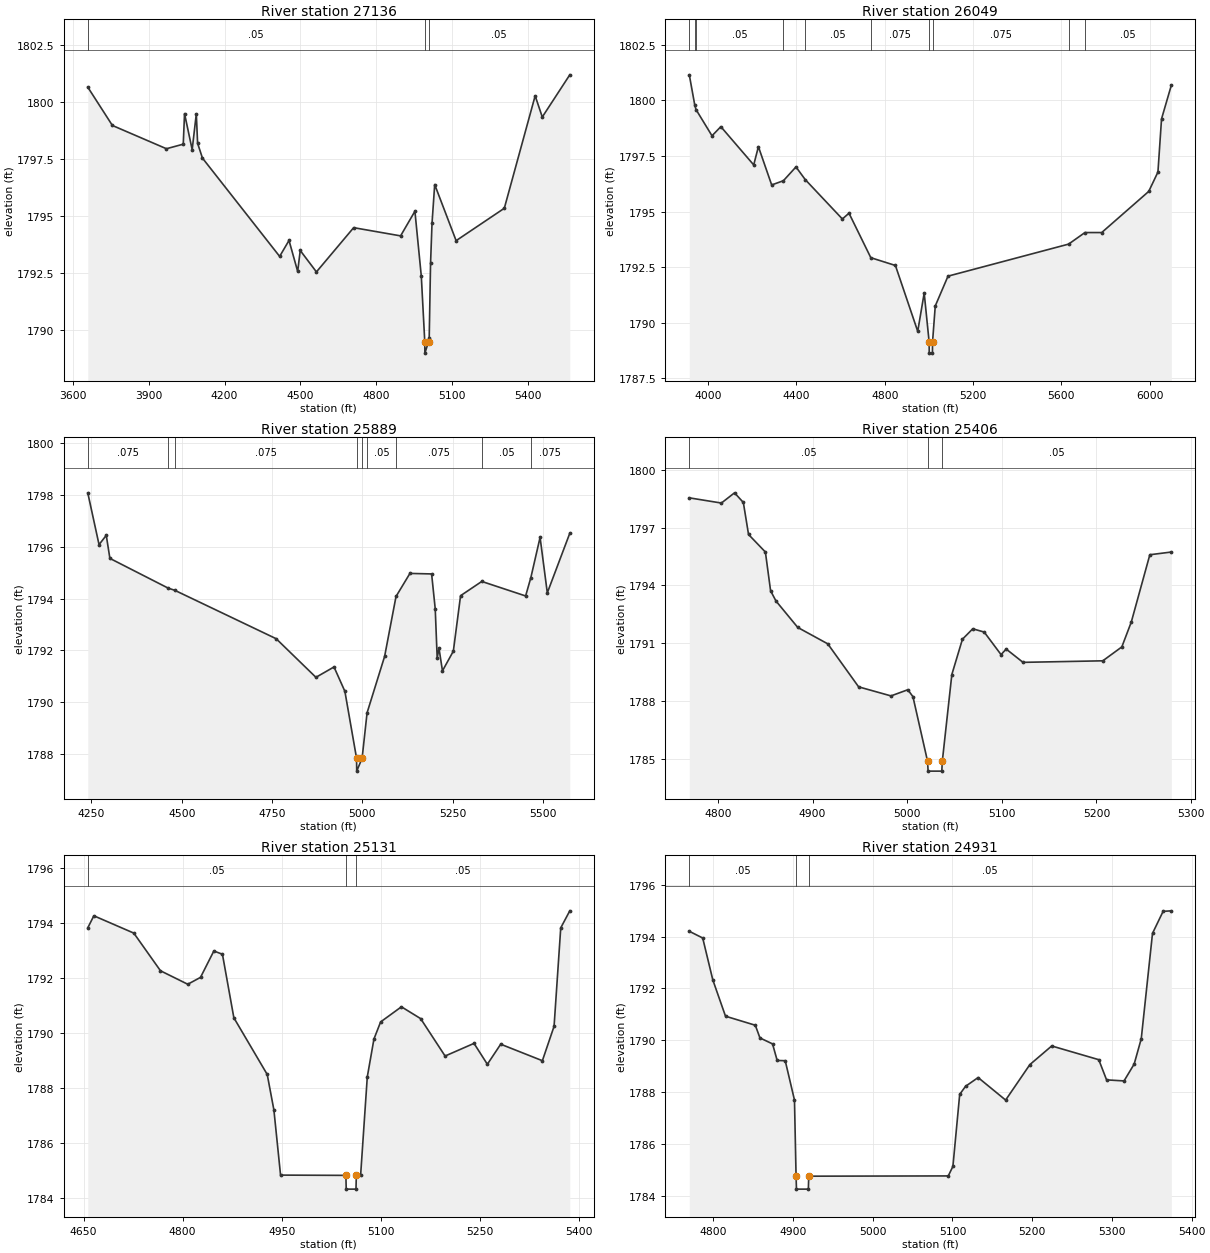
Type RM Length L Ch R = 1 ,27136   ,1087,1087,1087
BEGIN DESCRIPTION:
Mapping XS 67269d83
END DESCRIPTION:
XS GIS Cut Line= 4
      1577569.27      6820320.92      1578597.92      6820520.57
      1579190.37      6820728.91      1579421.26       6820754.8
#Sta/Elev= 30
  3658.7 1800.64  3756.2 1798.96  3970.1 1797.94  4036.7 1798.14  4041.8 1799.48
    4072  1797.9  4088.4 1799.47  4093.5 1798.18  4112.7 1797.53  4418.3 1793.22
  4455.4 1793.92  4489.7 1792.56  4499.8 1793.48  4563.9 1792.54  4711.3 1794.48
  4897.1 1794.12  4953.8  1795.2  4979.1 1792.35  4992.8 1789.48  4993.3 1788.98
  5007.7 1789.48  5010.4 1789.65  5015.7 1792.91  5021.5 1794.67  5032.1 1796.37
  5116.9 1793.91  5307.7 1795.33  5429.8 1800.26    5458 1799.33  5566.9 1801.18
#Mann= 3 ,-1 , 0
  3658.7     .05       0  4992.8     .05       0  5007.7     .05       0
Bank Sta=4992.8,5007.7
XS Rating Curve= 0 ,0
Exp/Cntr=0.3,0.1

Type RM Length L Ch R = 1 ,26049   ,160,160,160
BEGIN DESCRIPTION:
Mapping XS 126a32fc
END DESCRIPTION:
XS GIS Cut Line= 4
      1577122.23      6820943.75      1578022.83      6820971.96
      1578801.91      6820917.71      1579288.06      6820798.34
#Sta/Elev= 30
  3915.2 1801.15  3939.8  1799.8  3945.5 1799.59    4018 1798.41    4058 1798.82
  4206.9  1797.1  4228.1 1797.92  4288.2  1796.2  4341.3 1796.39  4398.2 1797.01
  4440.2 1796.44  4608.3 1794.67  4638.3 1794.93  4737.1 1792.93  4848.5 1792.58
  4949.5 1789.62  4978.8 1791.34  5001.2 1789.14  5001.7 1788.64  5016.1 1788.64
  5016.6 1789.14  5028.9 1790.76  5086.6  1792.1  5632.6 1793.54  5706.7 1794.06
  5782.6 1794.06  5995.6 1795.91  6037.2 1796.78  6053.5 1799.17  6097.8 1800.68
#Mann= 10 ,-1 , 0
  3915.2     .05       0  3939.8    .075       0  3945.5     .05       0
  4341.3    .075       0  4440.2     .05       0  4737.1    .075       0
  5001.2     .07       0  5016.6    .075       0  5632.6    .075       0
  5706.7     .05       0
Bank Sta=5001.2,5016.6
XS Rating Curve= 0 ,0
Exp/Cntr=0.3,0.1

Type RM Length L Ch R = 1 ,25889   ,483,483,483
BEGIN DESCRIPTION:
Mapping XS 02714200
END DESCRIPTION:
XS GIS Cut Line= 3
      1577443.85      6821115.63      1577909.12      6821126.04
      1578777.14      6821103.47
#Sta/Elev= 30
  4240.1 1798.08  4271.3 1796.08  4291.3 1796.44  4301.3 1795.55  4462.9  1794.4
  4480.6 1794.32  4761.4 1792.45  4871.4 1790.96  4921.4 1791.36  4951.5 1790.42
  4983.8 1787.84  4984.3 1787.34  4999.2 1787.84  5012.9 1789.59  5061.5 1791.77
    5093 1794.08  5131.5 1794.97  5191.5 1794.95  5201.5  1793.6  5206.9 1791.71
  5211.9 1792.08  5221.5 1791.21  5251.6 1791.97  5271.6 1794.11  5330.3 1794.66
  5451.6  1794.1  5466.1 1794.81  5491.6 1796.36  5511.6 1794.22  5573.8 1796.52
#Mann= 9 ,-1 , 0
  4240.1    .075       0  4462.9     .05       0  4480.6    .075       0
  4983.8     .07       0  4999.2    .075       0  5012.9     .05       0
    5093    .075       0  5330.3     .05       0  5466.1    .075       0
Bank Sta=4983.8,4999.2
XS Rating Curve= 0 ,0
Exp/Cntr=0.3,0.1

Type RM Length L Ch R = 1 ,25406   ,275,275,275
BEGIN DESCRIPTION:
Mapping XS 9283d0a7
END DESCRIPTION:
XS GIS Cut Line= 5
      1577711.32      6821378.22      1578062.87      6821534.46
      1578169.21      6821527.95      1578173.55      6821527.95
      1578186.56      6821523.61
#Sta/Elev= 30
  4769.8 1798.54  4803.7 1798.27  4817.6  1798.8  4826.9  1798.3  4832.4 1796.64
  4850.2 1795.73  4855.7 1793.72  4861.4 1793.19  4884.4 1791.82  4916.1 1790.97
  4948.7 1788.74  4982.9 1788.27  5000.7 1788.59  5006.1 1788.23  5021.6 1784.87
  5022.1 1784.37  5036.6 1784.37  5037.1 1784.87  5047.2 1789.38  5058.4 1791.21
  5069.3 1791.75  5081.4 1791.58  5099.2 1790.41  5104.6  1790.7  5122.4 1790.01
  5206.7 1790.09  5226.8 1790.81  5236.8  1792.1  5256.4 1795.59  5279.1 1795.73
#Mann= 3 ,-1 , 0
  4769.8     .05       0  5021.6     .03       0  5037.1     .05       0
Bank Sta=5021.6,5037.1
XS Rating Curve= 0 ,0
Exp/Cntr=0.3,0.1

Type RM Length L Ch R = 1 ,25131   ,200,200,200
BEGIN DESCRIPTION:
Mapping XS 2c882516
END DESCRIPTION:
XS GIS Cut Line= 3
      1577515.97      6821712.41      1577715.65      6821740.63
      1578238.61      6821666.85
#Sta/Elev= 30
  4656.4 1793.81  4665.6 1794.25  4726.1 1793.62  4766.5 1792.25  4807.8 1791.76
  4827.1 1792.01  4847.3 1792.97  4860.3 1792.85  4877.6 1790.54  4928.1 1788.48
  4938.2 1787.19  4948.3 1784.82  5047.2 1784.81  5047.7 1784.31  5062.5 1784.31
    5063 1784.81  5069.5 1784.81  5079.6 1788.39  5089.7 1789.77  5099.8 1790.39
  5131.3 1790.94  5160.4 1790.51  5197.4 1789.15  5241.2 1789.61  5261.4 1788.85
  5281.6 1789.58  5344.7 1788.98  5362.4 1790.23  5372.5 1793.81  5386.2 1794.43
#Mann= 3 ,-1 , 0
  4656.4     .05       0  5047.2     .03       0    5063     .05       0
Bank Sta=5047.2,5063
XS Rating Curve= 0 ,0
Exp/Cntr=0.3,0.1

Type RM Length L Ch R = 1 ,24931   ,270,270,270
BEGIN DESCRIPTION:
Mapping XS 74fd1e86
END DESCRIPTION:
XS GIS Cut Line= 2
      1577750.39      6822005.37      1578275.51      6821705.92
#Sta/Elev= 30
    4770 1794.21  4786.8 1793.95  4799.5 1792.33  4815.4 1790.93  4852.8 1790.58
  4858.6 1790.09  4874.4 1789.86  4880.2 1789.22  4890.3 1789.21  4901.9 1787.69
  4903.9 1784.75  4904.4 1784.25  4919.3 1784.25  4919.8 1784.75  5094.8 1784.76
  5100.6 1785.13  5109.1 1787.91  5116.4 1788.22  5132.2 1788.56  5166.7 1787.69
  5197.1 1789.06  5224.5 1789.78  5283.5 1789.25  5293.3 1788.47  5315.2 1788.43
  5327.9 1789.08  5336.8 1790.06  5350.9 1794.13  5364.2 1794.98  5374.5    1795
#Mann= 3 ,-1 , 0
    4770     .05       0  4903.9     .03       0  4919.8     .05       0
Bank Sta=4903.9,4919.8
XS Rating Curve= 0 ,0
Exp/Cntr=0.3,0.1

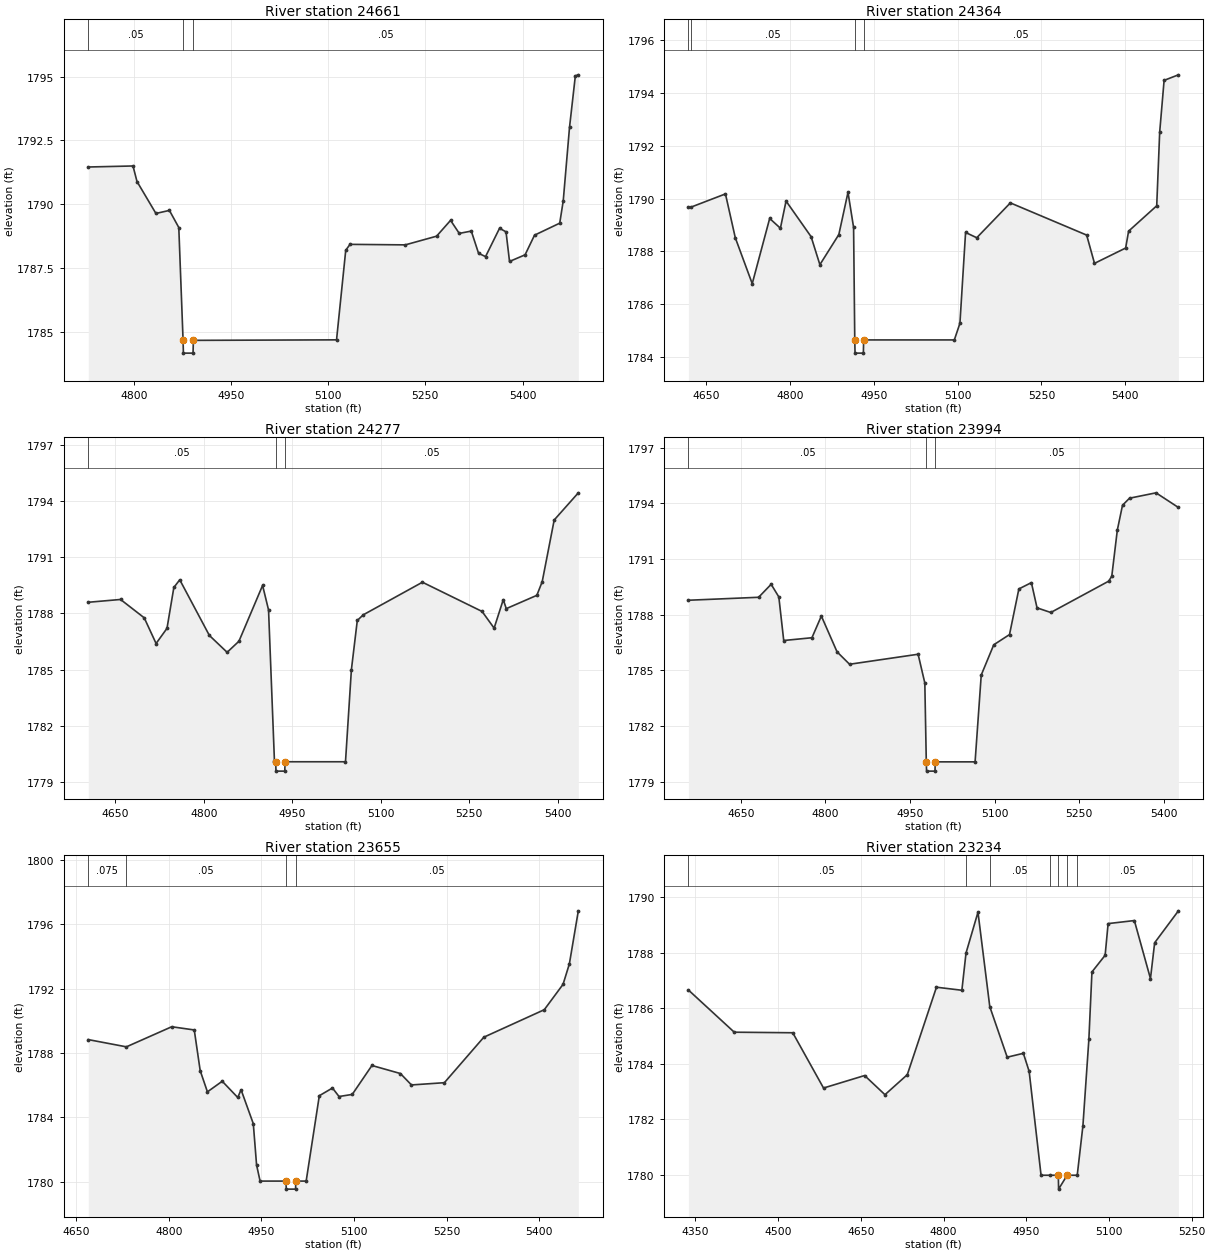
Type RM Length L Ch R = 1 ,24661   ,297,297,297
BEGIN DESCRIPTION:
Mapping XS d721c8f4
END DESCRIPTION:
XS GIS Cut Line= 3
      1577798.15        6822307.      1578190.91      6822009.72
      1578290.38      6821765.37
#Sta/Elev= 30
  4729.7 1791.46  4798.7  1791.5  4804.9 1790.89  4834.1 1789.64  4854.9 1789.76
  4869.4 1789.09    4876 1784.67  4876.5 1784.17  4891.4 1784.17  4891.9 1784.67
  5112.9 1784.69  5127.1  1788.2  5133.7 1788.43    5219 1788.41  5267.3 1788.75
  5288.9 1789.37  5302.3 1788.86  5320.9 1788.95  5332.1 1788.08  5342.9 1787.95
  5364.5 1789.06  5374.5 1788.92  5379.9 1787.76  5403.9 1788.02  5418.5 1788.79
  5457.4 1789.26  5462.8 1790.13  5472.5 1793.01  5481.5 1795.03  5486.1 1795.07
#Mann= 3 ,-1 , 0
  4729.7     .05       0    4876     .03       0  4891.9     .05       0
Bank Sta=4876,4891.9
XS Rating Curve= 0 ,0
Exp/Cntr=0.3,0.1

Type RM Length L Ch R = 1 ,24364   ,87,87,87
BEGIN DESCRIPTION:
Mapping XS 8044fc9d
END DESCRIPTION:
XS GIS Cut Line= 4
      1578201.76      6822641.21      1578236.48      6822374.31
      1578219.12      6822037.93      1578312.44      6821784.01
#Sta/Elev= 30
  4618.5 1789.67  4623.3 1789.68  4684.8 1790.18  4702.4 1788.52  4732.7 1786.78
  4763.9 1789.25  4783.1 1788.88  4793.2 1789.91    4838 1788.56  4853.7  1787.5
  4887.6 1788.64    4904 1790.24    4914 1788.91  4916.1 1784.65  4916.6 1784.15
  4931.5 1784.15    4932 1784.65  5094.2 1784.65  5104.2 1785.28  5114.3 1788.72
  5134.3 1788.52  5194.4 1789.84  5330.9 1788.62  5344.9 1787.55  5400.6 1788.13
  5405.9 1788.77  5456.2 1789.73  5461.5 1792.52  5469.4 1794.48    5495 1794.69
#Mann= 4 ,-1 , 0
  4618.5    .075       0  4623.3     .05       0  4916.1     .03       0
    4932     .05       0
Bank Sta=4916.1,4932
XS Rating Curve= 0 ,0
Exp/Cntr=0.3,0.1

Type RM Length L Ch R = 1 ,24277   ,283,283,283
BEGIN DESCRIPTION:
Mapping XS 3340c2d6
END DESCRIPTION:
XS GIS Cut Line= 3
      1578340.65      6822632.55       1578292.9      6822020.57
      1578334.14      6821807.87
#Sta/Elev= 30
  4604.4 1788.59  4659.1 1788.74  4699.2 1787.76  4719.3 1786.39  4737.8  1787.2
  4749.4 1789.38  4759.4 1789.79  4809.6 1786.82  4839.7 1785.92  4859.7 1786.51
  4899.8 1789.49  4909.9 1788.18  4919.9 1780.11    4922 1780.08  4922.5 1779.58
  4937.4 1779.58  4937.9 1780.08  5040.3 1780.08  5050.3 1784.99  5060.3 1787.62
  5070.4 1787.92  5170.7 1789.66  5271.8  1788.1  5292.2 1787.21  5307.7 1788.73
  5312.8 1788.25  5364.6 1788.96  5373.7 1789.69    5394 1792.98  5434.9 1794.43
#Mann= 3 ,-1 , 0
  4604.4     .05       0    4922     .03       0  4937.9     .05       0
Bank Sta=4922,4937.9
XS Rating Curve= 0 ,0
Exp/Cntr=0.3,0.1

Type RM Length L Ch R = 1 ,23994   ,339,339,339
BEGIN DESCRIPTION:
Mapping XS 6eef8ac6
END DESCRIPTION:
XS GIS Cut Line= 3
      1578381.87      6822660.79        1578664.      6822107.38
      1578755.14      6821877.36
#Sta/Elev= 30
  4557.2 1788.78  4681.7 1788.94  4703.9 1789.64  4717.5 1788.96  4726.2 1786.61
  4776.2 1786.76  4792.9 1787.93  4820.7    1786  4842.9 1785.33  4964.4 1785.87
  4976.3 1784.32  4978.9 1780.07  4979.4 1779.57  4994.3 1779.57  4994.8 1780.07
  5065.4 1780.07  5076.3 1784.75  5098.5 1786.38  5126.4 1786.93    5143 1789.39
  5165.2 1789.73  5175.2 1788.37  5199.6 1788.12  5302.3 1789.81  5307.7 1790.08
  5317.5 1792.56  5326.7  1793.9  5339.1 1794.28  5386.1 1794.57  5425.8 1793.78
#Mann= 3 ,-1 , 0
  4557.2     .05       0  4978.9     .03       0  4994.8     .05       0
Bank Sta=4978.9,4994.8
XS Rating Curve= 0 ,0
Exp/Cntr=0.3,0.1

Type RM Length L Ch R = 1 ,23655   ,421,421,421
BEGIN DESCRIPTION:
Mapping XS 82207c9d
END DESCRIPTION:
XS GIS Cut Line= 3
      1578427.43      6822728.06      1578520.77      6822630.38
      1579138.57      6822402.77
#Sta/Elev= 30
  4669.7 1788.84  4731.4 1788.39  4804.8 1789.64  4841.3 1789.44  4850.9 1786.91
  4862.6 1785.59  4886.6 1786.25  4911.7 1785.24  4917.1 1785.72  4936.9 1783.61
  4942.2 1781.04  4947.9 1780.04  4989.8 1780.04  4990.3 1779.54  5005.3 1779.54
  5005.8 1780.04  5022.5 1780.04  5043.8 1785.35  5065.1 1785.83  5075.7  1785.3
  5097.1 1785.43    5129 1787.23  5175.1 1786.73    5193 1786.02  5246.3 1786.16
  5310.2 1788.99  5408.1  1790.7  5438.5 1792.28  5448.7 1793.55  5463.2 1796.85
#Mann= 4 ,-1 , 0
  4669.7    .075       0  4731.4     .05       0  4989.8     .03       0
  5005.8     .05       0
Bank Sta=4989.8,5005.8
XS Rating Curve= 0 ,0
Exp/Cntr=0.3,0.1

Type RM Length L Ch R = 1 ,23234   ,405,405,405
BEGIN DESCRIPTION:
Mapping XS 2d9c86be
END DESCRIPTION:
XS GIS Cut Line= 3
      1578342.85      6823012.32      1578826.76      6822936.37
      1579194.81      6822782.66
#Sta/Elev= 30
  4337.2 1786.66  4420.4 1785.14  4526.5 1785.12  4582.3 1783.13  4656.8 1783.58
  4693.7 1782.89  4734.2 1783.61  4787.1 1786.76  4833.2 1786.65  4840.7 1787.99
  4862.4 1789.46  4883.8 1786.06  4915.4 1784.24  4944.7 1784.38  4955.2 1783.73
  4976.8 1779.99  4992.3 1779.99  5008.1 1779.99  5008.6 1779.49  5024.1 1779.99
  5042.4 1779.99  5052.7 1781.77  5063.5 1784.88  5069.1 1787.31    5093 1787.91
  5098.4 1789.05    5146 1789.16  5175.2 1787.07  5182.8 1788.36  5225.9 1789.51
#Mann= 7 ,-1 , 0
  4337.2     .05       0  4840.7     .12       0  4883.8     .05       0
  4992.3     .12       0  5008.1     .07       0  5024.1     .12       0
  5042.4     .05       0
Bank Sta=5008.1,5024.1
XS Rating Curve= 0 ,0
Exp/Cntr=0.3,0.1

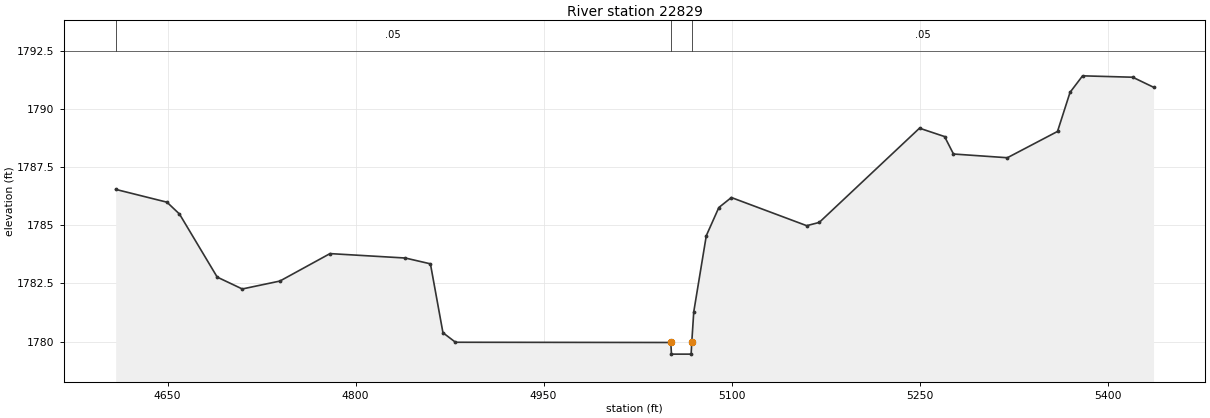
Type RM Length L Ch R = 1 ,22829   ,307,307,307
BEGIN DESCRIPTION:
Mapping XS 2a6bbc22
END DESCRIPTION:
XS GIS Cut Line= 2
       1578614.1      6823257.55      1579441.54      6823227.23
#Sta/Elev= 30
  4608.6 1786.54  4649.5 1785.99  4659.5 1785.48  4689.6 1782.77  4709.6 1782.26
  4739.6  1782.6  4779.6 1783.78  4839.7 1783.59  4859.7 1783.34  4869.7 1780.38
  4879.7 1779.97  5051.5 1779.96    5052 1779.46  5067.7 1779.46  5068.2 1779.96
  5069.8 1781.28  5079.8 1784.55  5089.8 1785.76  5099.8 1786.19  5159.9 1784.98
  5169.9 1785.12  5249.9 1789.17  5269.9 1788.81    5277 1788.06    5320  1787.9
    5360 1789.03    5370 1790.71    5380 1791.42    5420 1791.36  5436.6 1790.93
#Mann= 3 ,-1 , 0
  4608.6     .05       0  5051.5     .05       0  5068.2     .05       0
Bank Sta=5051.5,5068.2
XS Rating Curve= 0 ,0
Exp/Cntr=0.3,0.1