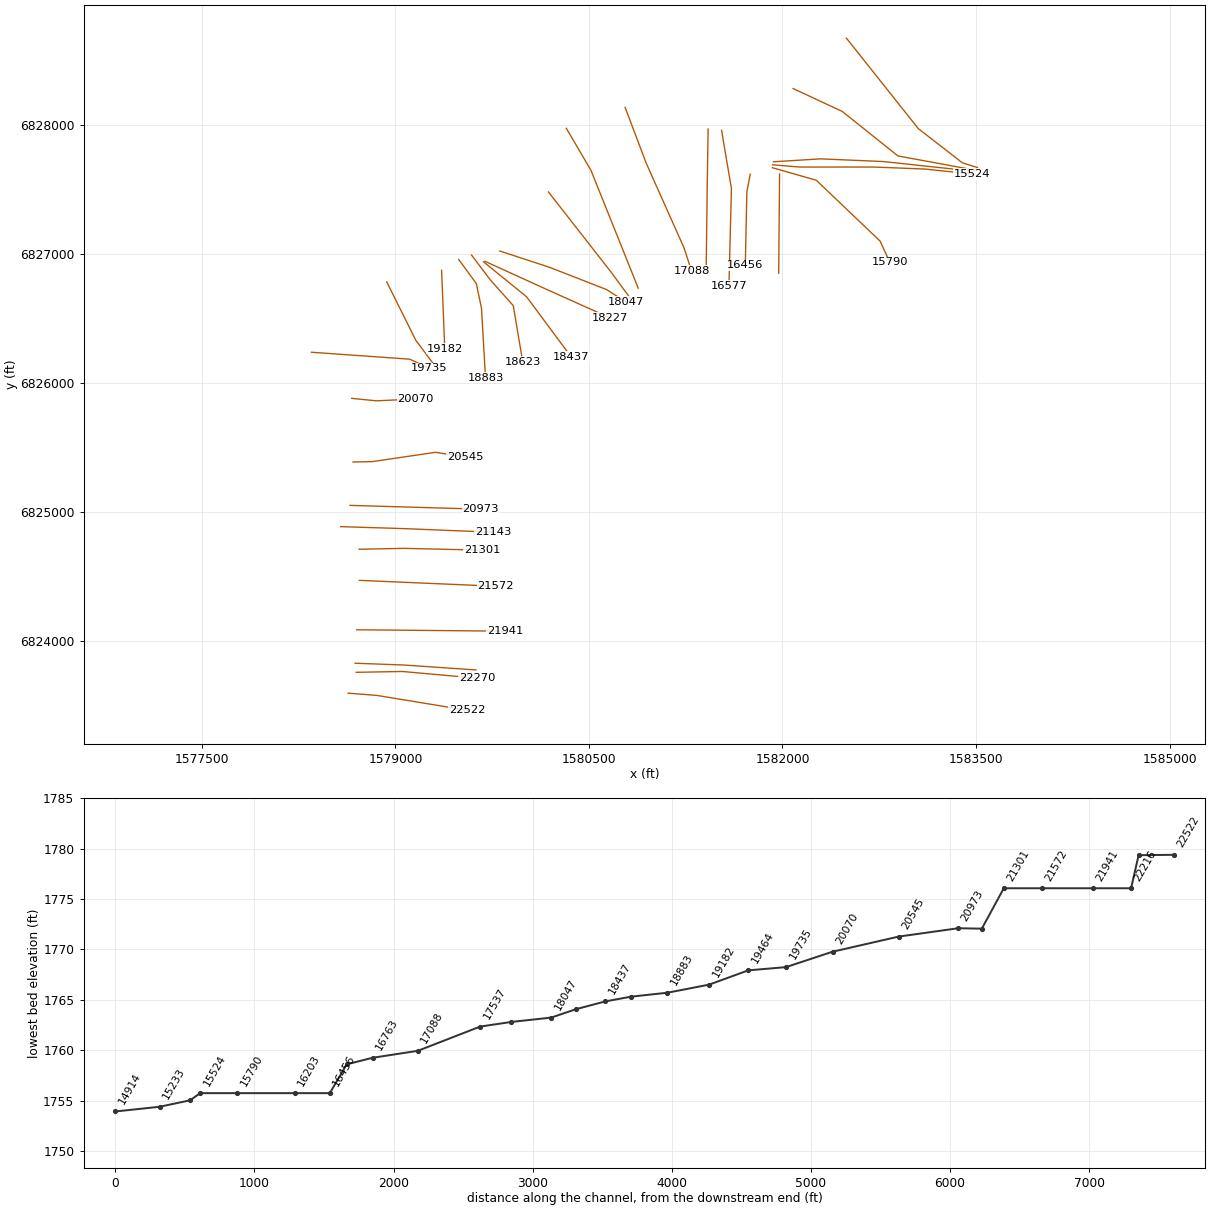
HEC-RAS study Buttonwillow Creek.prj: Buttonwillow Creek Base Level Engineering

--- Buttonwillow Creek.g01 (geometry) --- (continued)

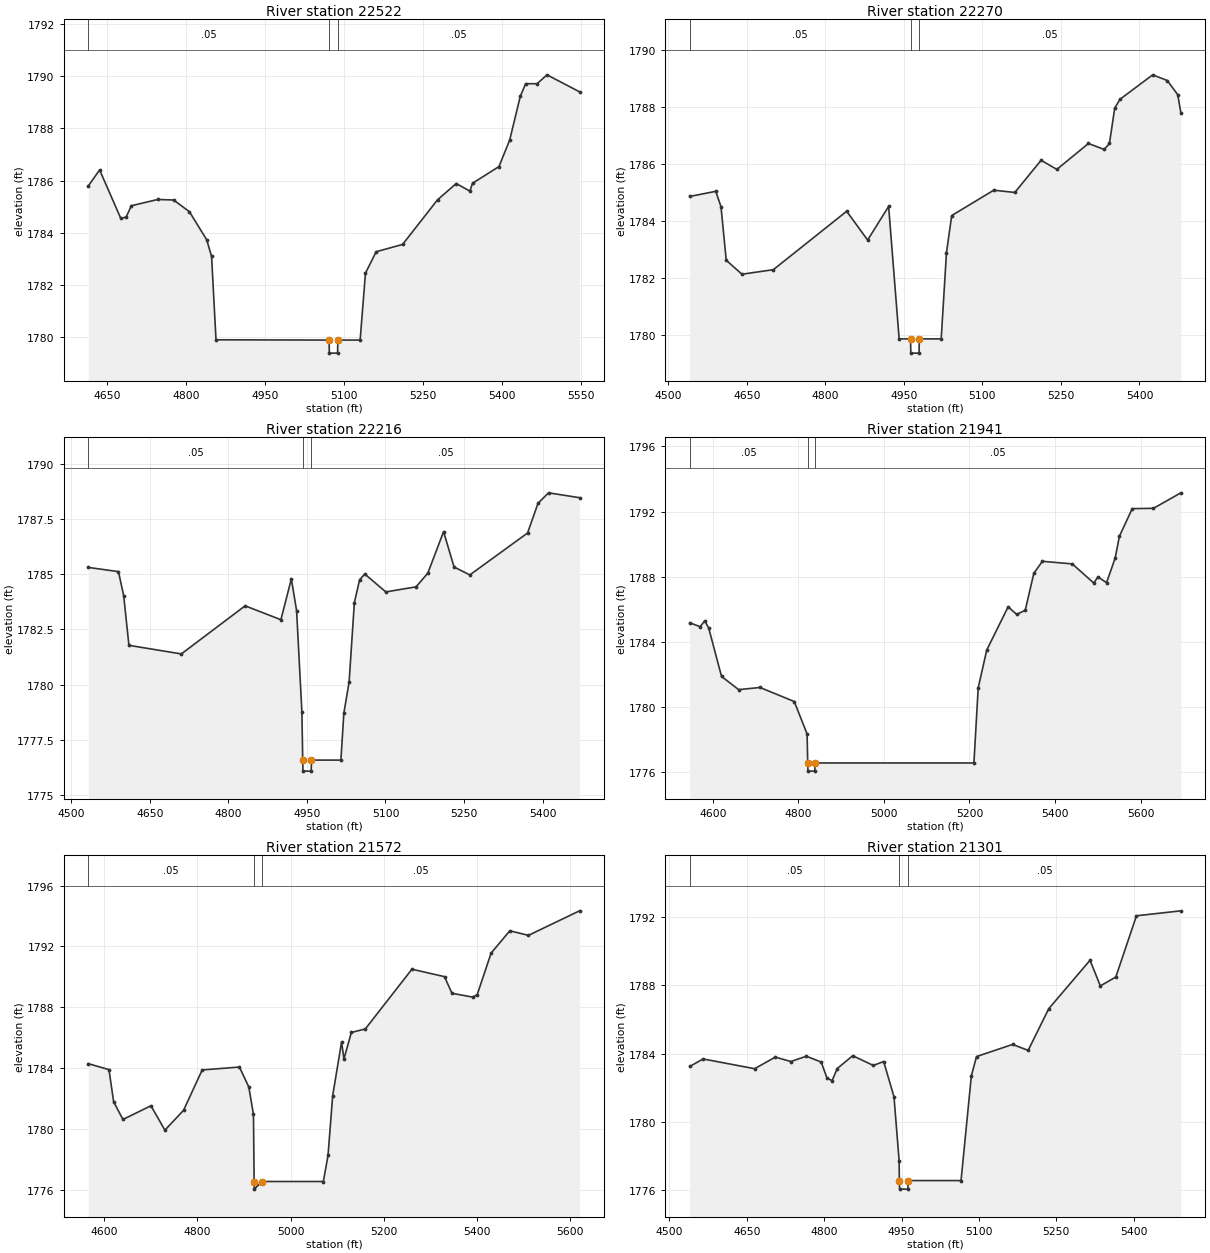
Type RM Length L Ch R = 1 ,22522   ,252,252,252
BEGIN DESCRIPTION:
Mapping XS 98c63d16
END DESCRIPTION:
XS GIS Cut Line= 3
      1578633.64      6823591.75      1578854.97      6823574.39
      1579555.89      6823459.38
#Sta/Elev= 30
  4615.1  1785.8  4636.5 1786.41  4676.6 1784.56  4686.7  1784.6  4696.7 1785.04
  4746.9 1785.28    4777 1785.26    4807 1784.81  4839.7 1783.74    4849  1783.1
  4857.4 1779.91    5072  1779.9  5072.5  1779.4  5088.2  1779.4  5088.7  1779.9
    5131  1779.9  5141.1 1782.46  5161.4 1783.28  5211.6 1783.56    5278 1785.27
  5313.4 1785.89  5339.3  1785.6  5344.3  1785.9  5394.5 1786.54  5414.8 1787.55
    5435 1789.23  5445.2 1789.71  5466.9 1789.71  5485.7 1790.05  5547.4  1789.4
#Mann= 3 ,-1 , 0
  4615.1     .05       0    5072     .03       0  5088.7     .05       0
Bank Sta=5072,5088.7
XS Rating Curve= 0 ,0
Exp/Cntr=0.3,0.1

Type RM Length L Ch R = 1 ,22270   ,54,54,54
BEGIN DESCRIPTION:
Mapping XS ea1e307c
END DESCRIPTION:
XS GIS Cut Line= 3
      1578695.24      6823753.43      1579053.27      6823759.94
      1579630.84      6823707.93
#Sta/Elev= 30
  4541.1 1784.86  4590.9 1785.04  4600.9  1784.5  4610.9 1782.62  4640.9 1782.13
  4700.9 1782.29  4840.9 1784.34  4880.9 1783.33    4921 1784.51  4941.1 1779.86
  4962.9 1779.86  4963.4 1779.36  4979.1 1779.36  4979.6 1779.86  5021.4 1779.86
  5031.5 1782.89  5041.5 1784.19  5121.8 1785.08    5162    1785  5212.2 1786.13
  5242.3 1785.81  5302.6 1786.72  5332.7 1786.51  5342.7 1786.72  5352.8 1787.96
  5362.8 1788.27  5425.3 1789.13  5453.2 1788.93  5473.2 1788.43  5479.1  1787.8
#Mann= 3 ,-1 , 0
  4541.1     .05       0  4962.9     .03       0  4979.6     .05       0
Bank Sta=4962.9,4979.6
XS Rating Curve= 0 ,0
Exp/Cntr=0.3,0.1

Type RM Length L Ch R = 1 ,22216   ,275,275,275
BEGIN DESCRIPTION:
Mapping XS fb6b2c9f
END DESCRIPTION:
XS GIS Cut Line= 3
      1578687.57      6823823.96      1579068.46      6823809.85
      1579624.01      6823771.88
#Sta/Elev= 30
  4532.6 1785.31  4590.1 1785.12  4600.1 1784.03  4610.1 1781.78  4710.2 1781.39
    4832 1783.57  4900.3 1782.94  4920.3 1784.79  4930.3 1783.35  4940.4 1778.77
    4942 1776.58  4942.5 1776.08  4958.2 1776.08  4958.7 1776.58  5014.9 1776.58
  5020.5  1778.7  5030.6 1780.12  5040.6 1783.71  5050.6 1784.75  5060.6 1785.01
  5100.7  1784.2  5158.4 1784.43  5180.9 1785.05    5211 1786.93    5231 1785.33
  5261.1 1784.97  5371.4 1786.87  5391.4 1788.22  5411.5 1788.69  5470.6 1788.47
#Mann= 3 ,-1 , 0
  4532.6     .05       0    4942     .03       0  4958.7     .05       0
Bank Sta=4942,4958.7
XS Rating Curve= 0 ,0
Exp/Cntr=0.3,0.1

Type RM Length L Ch R = 1 ,21941   ,369,369,369
BEGIN DESCRIPTION:
Mapping XS 66fb4c77
END DESCRIPTION:
XS GIS Cut Line= 2
      1578700.59      6824083.29      1579848.64      6824072.44
#Sta/Elev= 30
    4546 1785.18  4570.4 1784.94  4581.1  1785.3  4590.4 1784.86  4620.4 1781.89
  4660.4 1781.08  4710.4 1781.21  4790.4 1780.35  4820.4 1778.36  4821.9 1776.58
  4822.4 1776.08  4838.4 1776.08  4838.9 1776.58  5210.4 1776.58  5220.4 1781.19
  5240.4 1783.51  5290.4 1786.16  5310.4 1785.69  5330.4 1785.95  5350.4 1788.21
  5370.4 1788.95  5440.4 1788.79  5490.4 1787.62  5500.4 1787.99  5520.4 1787.64
  5540.5 1789.14  5550.5 1790.49  5580.5 1792.18  5630.1  1792.2  5694.1 1793.15
#Mann= 3 ,-1 , 0
    4546     .05       0  4821.9     .03       0  4838.9     .05       0
Bank Sta=4821.9,4838.9
XS Rating Curve= 0 ,0
Exp/Cntr=0.3,0.1

Type RM Length L Ch R = 1 ,21572   ,271,271,271
BEGIN DESCRIPTION:
Mapping XS 99d52b1d
END DESCRIPTION:
XS GIS Cut Line= 2
      1578720.76      6824466.45       1579774.6      6824421.31
#Sta/Elev= 30
  4565.7 1784.31    4610 1783.92    4620 1781.81    4640 1780.65  4700.1 1781.55
  4730.1 1779.95  4770.1 1781.25  4810.2  1783.9  4890.2 1784.09  4910.3 1782.78
  4920.3 1780.98  4921.7 1776.58  4922.2 1776.08  4938.8 1776.58  5070.4 1776.58
  5080.4 1778.29  5090.4 1782.21  5109.5 1785.73  5114.6 1784.62  5130.5 1786.36
  5160.5 1786.59  5260.6 1790.51  5330.6 1790.02  5346.5 1788.93  5390.7 1788.68
  5400.7 1788.83  5430.7 1791.57  5470.8 1793.03  5510.8 1792.73  5620.5 1794.34
#Mann= 3 ,-1 , 0
  4565.7     .05       0  4921.7     .03       0  4938.8     .05       0
Bank Sta=4921.7,4938.8
XS Rating Curve= 0 ,0
Exp/Cntr=0.3,0.1

Type RM Length L Ch R = 1 ,21301   ,158,158,158
BEGIN DESCRIPTION:
Mapping XS 06257182
END DESCRIPTION:
XS GIS Cut Line= 3
      1578718.99      6824707.77      1579062.77      6824714.71
      1579671.07      6824700.85
#Sta/Elev= 30
  4539.3 1783.25  4565.3 1783.69  4665.3 1783.12  4705.3  1783.8  4735.3 1783.54
  4765.4 1783.85  4794.3 1783.51  4805.4 1782.58  4815.4 1782.42  4825.4 1783.13
  4855.4 1783.88  4895.4 1783.31  4915.4 1783.54  4935.4 1781.48  4945.4 1777.73
  4945.8 1776.58  4946.3 1776.08  4962.4 1776.08  4962.9 1776.58  5065.4 1776.58
  5085.4  1782.7  5095.4 1783.83  5165.4 1784.54  5195.5 1784.19  5235.5 1786.63
  5315.5 1789.46  5335.5 1787.96  5365.5 1788.48  5405.5 1792.06  5491.6 1792.35
#Mann= 3 ,-1 , 0
  4539.3     .05       0  4945.8     .05       0  4962.9     .05       0
Bank Sta=4945.8,4962.9
XS Rating Curve= 0 ,0
Exp/Cntr=0.3,0.1

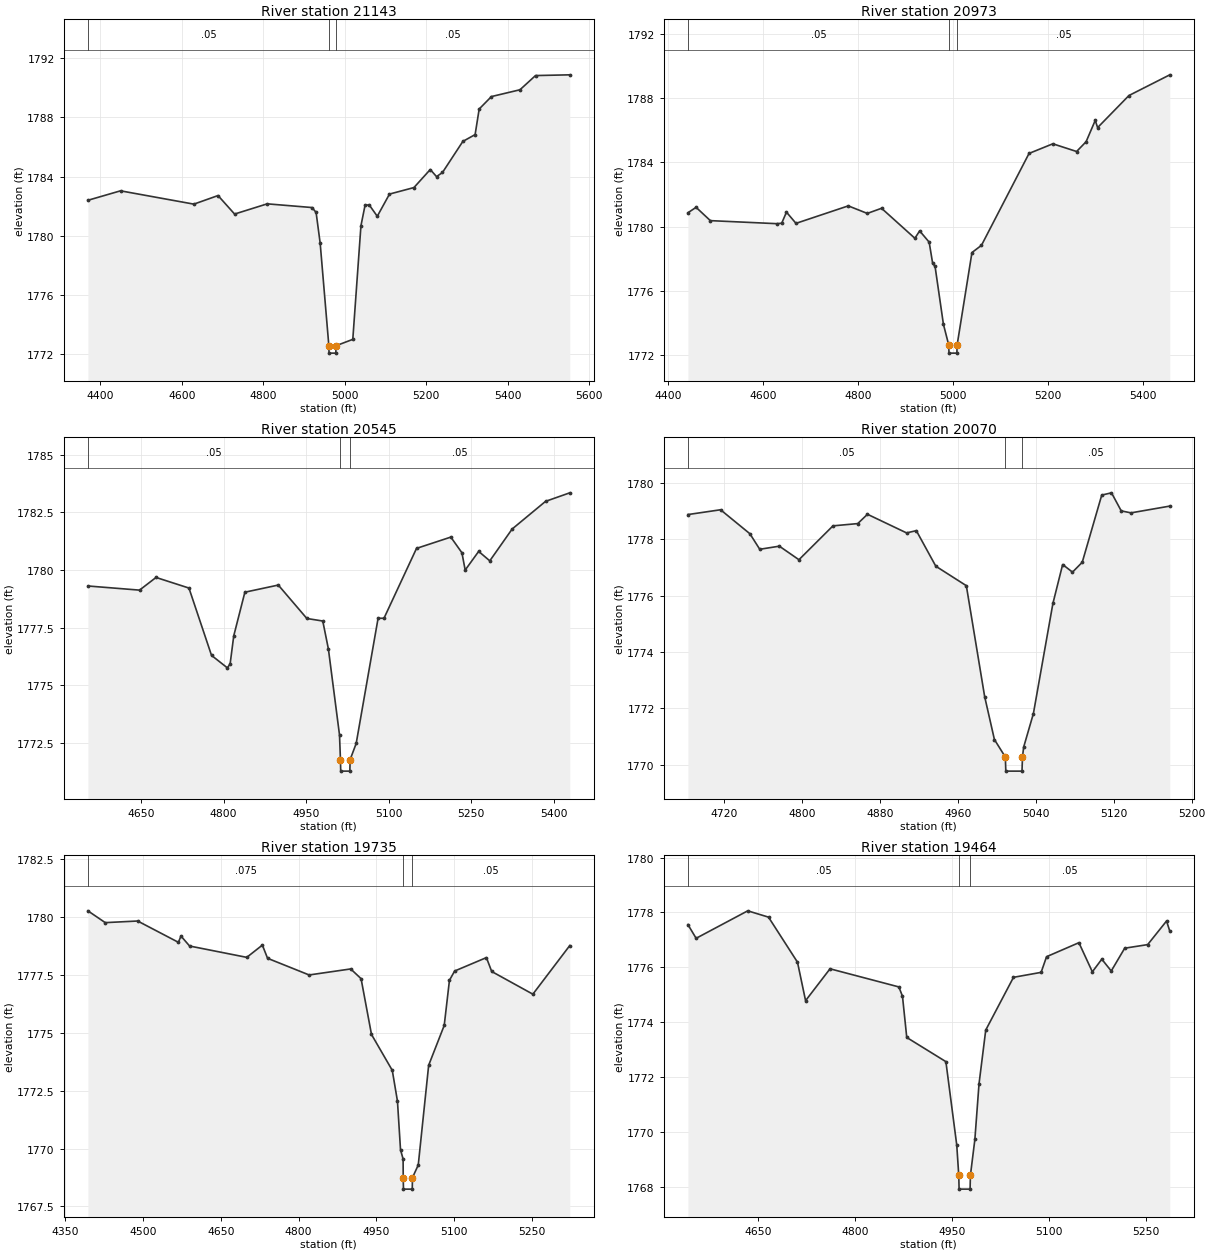
Type RM Length L Ch R = 1 ,21143   ,170,170,170
BEGIN DESCRIPTION:
Mapping XS 91d7a404
END DESCRIPTION:
XS GIS Cut Line= 3
      1578574.95      6824883.12      1579074.93      6824867.49
      1579757.25      6824839.71
#Sta/Elev= 30
  4369.7  1782.4  4449.8 1783.04  4629.9 1782.14  4689.2 1782.72  4729.9 1781.47
    4810 1782.16    4920 1781.91    4930 1781.58    4940  1779.5  4961.3 1772.57
  4961.8 1772.07  4978.4 1772.07  4978.9 1772.57  5020.1    1773  5040.1 1780.68
  5050.1 1782.05  5060.1  1782.1  5080.2 1781.32  5110.2 1782.82  5170.2 1783.26
  5210.3 1784.48  5225.7    1784  5240.3 1784.28  5290.3 1786.38  5320.4 1786.84
  5330.4 1788.57  5360.4 1789.41  5430.5 1789.87  5468.7 1790.83  5552.8 1790.88
#Mann= 3 ,-1 , 0
  4369.7     .05       0  4961.3     .05       0  4978.9     .05       0
Bank Sta=4961.3,4978.9
XS Rating Curve= 0 ,0
Exp/Cntr=0.3,0.1

Type RM Length L Ch R = 1 ,20973   ,428,428,428
BEGIN DESCRIPTION:
Mapping XS 99af9588
END DESCRIPTION:
XS GIS Cut Line= 2
      1578647.82      6825048.05       1579660.9      6825018.56
#Sta/Elev= 30
  4442.5 1780.86  4459.7  1781.2  4489.7 1780.37  4629.8 1780.18  4639.8 1780.21
  4649.8  1780.9  4669.8  1780.2  4779.8 1781.29  4819.8 1780.82  4849.8 1781.14
  4919.9 1779.27  4929.9 1779.73  4949.9 1779.03  4957.3  1777.7  4962.3 1777.52
  4979.9 1773.91  4991.1 1772.61  4991.6 1772.11  5008.2 1772.11  5008.7 1772.61
  5039.9 1778.38  5059.9 1778.83    5160 1784.56    5210 1785.16    5260 1784.68
    5280 1785.29  5299.2 1786.62  5304.2 1786.17  5370.1 1788.17    5456 1789.46
#Mann= 3 ,-1 , 0
  4442.5     .05       0  4991.1     .03       0  5008.7     .05       0
Bank Sta=4991.1,5008.7
XS Rating Curve= 0 ,0
Exp/Cntr=0.3,0.1

Type RM Length L Ch R = 1 ,20545   ,475,475,475
BEGIN DESCRIPTION:
Mapping XS dca4b294
END DESCRIPTION:
XS GIS Cut Line= 4
      1578671.24      6825384.62       1578818.8      6825387.12
      1579311.04      6825459.51      1579538.42      6825423.05
#Sta/Elev= 30
  4553.4 1779.31  4647.2 1779.13  4677.2 1779.68    4737 1779.22    4778  1776.3
  4806.7 1775.76  4811.8 1775.93  4818.4 1777.15  4838.6 1779.04  4899.3 1779.35
  4951.2  1777.9  4980.1 1777.79  4990.3 1776.58  5010.5 1772.85  5012.2 1771.78
  5012.7 1771.28  5029.3 1771.28  5029.8 1771.78  5040.8 1772.48  5080.6 1777.91
  5091.3 1777.91  5150.4 1780.94  5212.7 1781.43  5232.9 1780.75  5238.8    1780
  5263.3 1780.81  5283.5  1780.4  5324.1 1781.78  5384.8 1782.98  5428.8 1783.35
#Mann= 3 ,-1 , 0
  4553.4     .05       0  5012.2     .03       0  5029.8     .05       0
Bank Sta=5012.2,5029.8
XS Rating Curve= 0 ,0
Exp/Cntr=0.3,0.1

Type RM Length L Ch R = 1 ,20070   ,335,335,335
BEGIN DESCRIPTION:
Mapping XS 5bcbcc3d
END DESCRIPTION:
XS GIS Cut Line= 3
      1578661.72      6825877.91      1578850.97      6825858.81
      1579154.74       6825872.7
#Sta/Elev= 30
  4683.2 1778.87  4716.7 1779.04  4746.8 1778.19  4756.9 1777.64    4777 1777.75
  4797.1 1777.27    4832 1778.47  4857.4 1778.55  4867.4 1778.88  4907.5 1778.22
  4917.5  1778.3  4937.5 1777.04  4968.8 1776.35  4987.6 1772.42  4997.6  1770.9
  5008.8 1770.28  5009.3 1769.78  5025.9 1769.78  5026.4 1770.28  5027.6 1770.63
  5037.6 1771.82  5057.6 1775.72  5067.6  1777.1  5077.7 1776.83  5087.7 1777.18
  5107.7 1779.56  5117.7 1779.64  5127.7    1779  5137.7 1778.93  5177.5 1779.17
#Mann= 3 ,-1 , 0
  4683.2     .05       0  5008.8     .03       0  5026.4     .05       0
Bank Sta=5008.8,5026.4
XS Rating Curve= 0 ,0
Exp/Cntr=0.3,0.1

Type RM Length L Ch R = 1 ,19735   ,271,271,271
BEGIN DESCRIPTION:
Mapping XS a510139f
END DESCRIPTION:
XS GIS Cut Line= 3
      1578349.28      6826235.54      1579111.38      6826181.73
      1579261.18      6826111.13
#Sta/Elev= 30
  4393.4 1780.27  4426.9 1779.76  4489.4 1779.83    4568 1778.91    4573 1779.18
  4589.6 1778.75  4699.9 1778.26    4730 1778.79    4740 1778.22  4820.2  1777.5
  4900.4 1777.76  4920.4 1777.34  4940.5 1774.93  4980.6 1773.38  4990.6 1772.05
  4996.5 1769.95  5001.5 1769.55  5001.7 1768.75  5002.2 1768.25  5019.1 1768.25
  5019.6 1768.75  5030.7 1769.29  5050.8  1773.6  5080.8 1775.32  5090.9 1777.27
  5100.9 1777.67  5162.2 1778.25  5172.4 1777.65  5251.8 1776.67    5323 1778.77
#Mann= 3 ,-1 , 0
  4393.4    .075       0  5001.7     .07       0  5019.6     .05       0
Bank Sta=5001.7,5019.6
XS Rating Curve= 0 ,0
Exp/Cntr=0.3,0.1

Type RM Length L Ch R = 1 ,19464   ,282,282,282
BEGIN DESCRIPTION:
Mapping XS 2c56d77f
END DESCRIPTION:
XS GIS Cut Line= 3
      1578932.59      6826780.81      1579158.29      6826327.67
      1579301.21      6826136.54
#Sta/Elev= 30
  4541.7 1777.56  4554.4 1777.06  4634.2 1778.06  4666.3 1777.83  4711.1 1776.19
  4723.6 1774.79  4761.4 1775.95  4867.8 1775.29  4873.4 1774.95    4880 1773.45
  4940.5 1772.57  4957.3 1769.53  4960.4 1768.43  4960.9 1767.93  4977.9 1767.93
  4978.4 1768.43  4985.3 1769.74  4991.7 1771.76  5002.1 1773.72    5045 1775.64
  5087.7 1775.82  5096.1 1776.39  5146.1  1776.9  5166.9 1775.84  5181.5  1776.3
  5196.1 1775.87  5216.9  1776.7  5252.4 1776.83  5281.6 1777.69  5286.6 1777.32
#Mann= 3 ,-1 , 0
  4541.7     .05       0  4960.4     .05       0  4978.4     .05       0
Bank Sta=4960.4,4978.4
XS Rating Curve= 0 ,0
Exp/Cntr=0.3,0.1

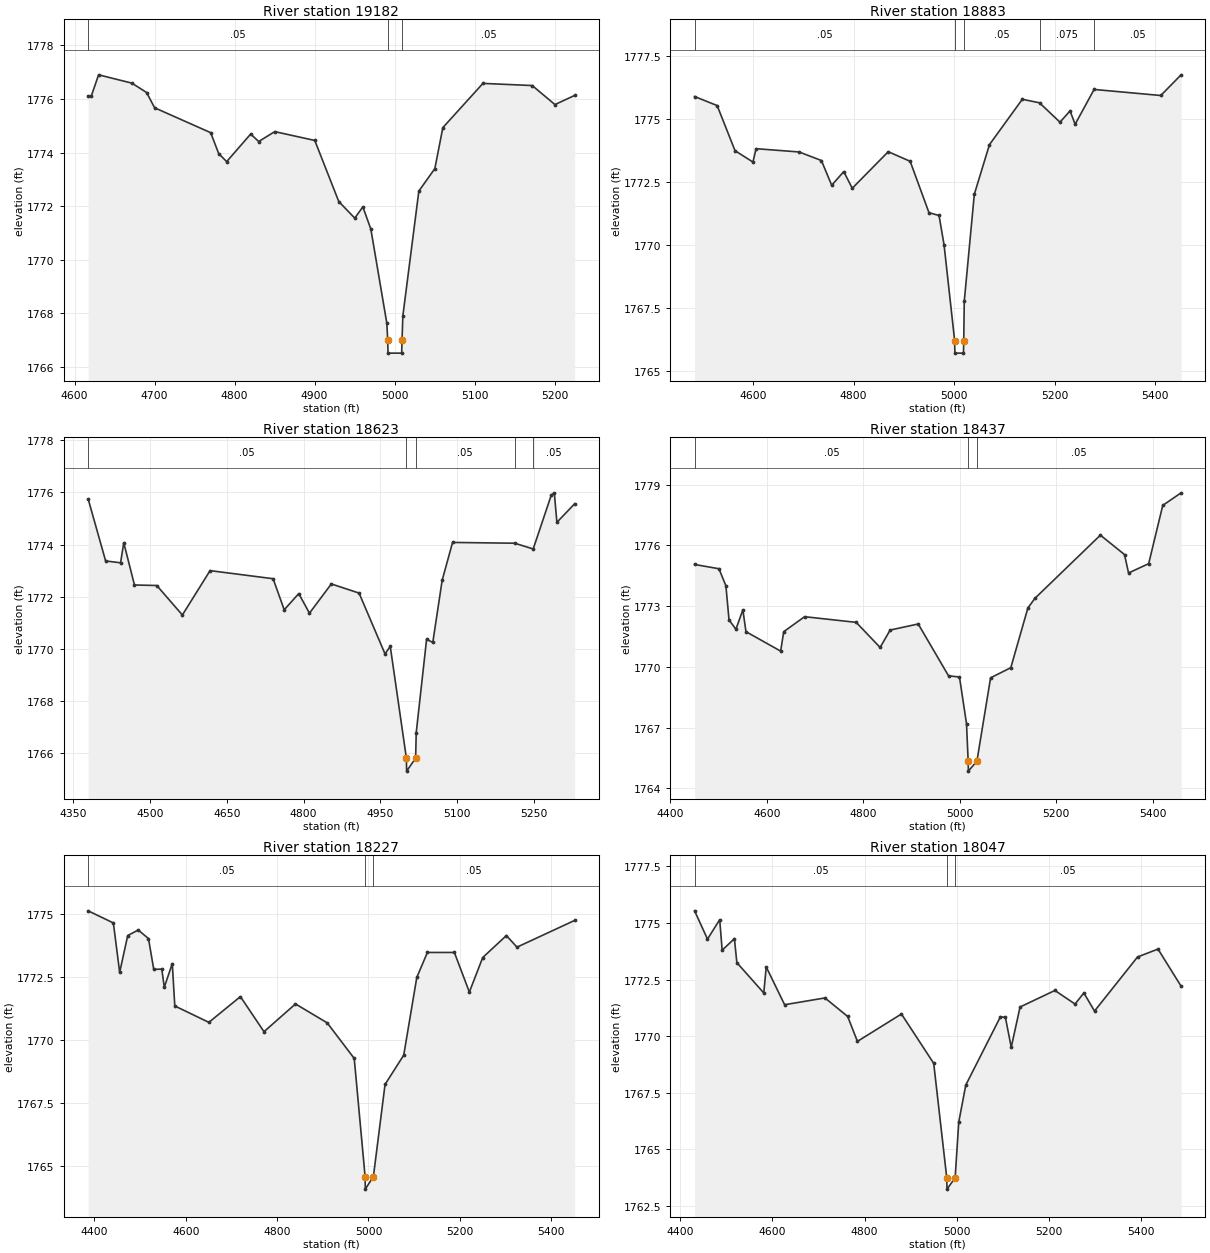
Type RM Length L Ch R = 1 ,19182   ,299,299,299
BEGIN DESCRIPTION:
Mapping XS 050a5c4a
END DESCRIPTION:
XS GIS Cut Line= 2
      1579357.95      6826871.08      1579382.25      6826263.46
#Sta/Elev= 30
    4617 1776.11    4621 1776.11  4630.1  1776.9  4671.7 1776.59  4690.1 1776.24
  4700.1 1775.67  4770.2 1774.74  4780.2 1773.96  4790.2 1773.66  4820.2 1774.69
  4830.2 1774.41  4850.3 1774.78  4900.3 1774.45  4930.3 1772.17  4950.3 1771.55
  4960.4 1771.97  4970.4 1771.14  4990.4 1767.62  4991.4 1767.01  4991.9 1766.51
  5008.9 1766.51  5009.4 1767.01  5010.4  1767.9  5030.4 1772.56  5050.4  1773.4
  5060.4 1774.93  5110.5 1776.58  5172.1  1776.5  5200.5 1775.79  5225.1 1776.13
#Mann= 3 ,-1 , 0
    4617     .05       0  4991.4     .05       0  5009.4     .05       0
Bank Sta=4991.4,5009.4
XS Rating Curve= 0 ,0
Exp/Cntr=0.3,0.1

Type RM Length L Ch R = 1 ,18883   ,260,260,260
BEGIN DESCRIPTION:
Mapping XS 7372326c
END DESCRIPTION:
XS GIS Cut Line= 4
      1579490.28      6826954.93      1579626.84      6826768.72
      1579666.98      6826577.67      1579698.23      6826037.72
#Sta/Elev= 30
    4484 1775.89  4528.9 1775.53  4564.4 1773.74    4600 1773.29  4606.2 1773.82
  4691.8 1773.69  4736.1 1773.35  4756.5 1772.37  4780.5 1772.91  4797.4 1772.25
  4868.9  1773.7  4912.5 1773.32  4949.9 1771.28  4969.9 1771.17  4979.9    1770
  5000.9 1766.21  5001.4 1765.71  5018.5 1765.71    5019 1766.21    5020 1767.76
    5040 1772.01  5070.1 1773.98  5135.4 1775.78  5169.6 1775.64  5210.3 1774.87
  5230.3 1775.32  5240.4 1774.79  5278.1 1776.17  5410.6 1775.93    5451 1776.75
#Mann= 5 ,-1 , 0
    4484     .05       0  5000.9     .05       0    5019     .05       0
  5169.6    .075       0  5278.1     .05       0
Bank Sta=5000.9,5019
XS Rating Curve= 0 ,0
Exp/Cntr=0.3,0.1

Type RM Length L Ch R = 1 ,18623   ,186,186,186
BEGIN DESCRIPTION:
Mapping XS 9f8ed024
END DESCRIPTION:
XS GIS Cut Line= 4
      1579589.21      6826990.13      1579735.07      6826797.38
       1579913.5      6826596.77       1579986.4      6826162.85
#Sta/Elev= 30
  4379.1 1775.75  4413.3 1773.37  4442.5  1773.3  4448.7 1774.07  4469.6 1772.45
  4513.2 1772.43  4563.2  1771.3  4617.3    1773  4740.4 1772.69  4762.1  1771.5
  4790.5 1772.12  4811.4 1771.37  4854.1 1772.49  4908.3 1772.14    4959 1769.81
  4969.2  1770.1  5000.7 1765.82  5001.2 1765.32  5018.8 1765.82  5019.9 1766.79
  5040.2 1770.37  5052.3 1770.25  5070.6 1772.63  5090.9 1774.08  5212.2 1774.05
  5248.4 1773.83  5283.5 1775.88  5289.6 1775.98  5294.7 1774.85  5329.3 1775.56
#Mann= 5 ,-1 , 0
  4379.1     .05       0  5000.7     .05       0  5018.8     .05       0
  5212.2    .075       0  5248.4     .05       0
Bank Sta=5000.7,5018.8
XS Rating Curve= 0 ,0
Exp/Cntr=0.3,0.1

Type RM Length L Ch R = 1 ,18437   ,210,210,210
BEGIN DESCRIPTION:
Mapping XS 6a4ded46
END DESCRIPTION:
XS GIS Cut Line= 3
        1579683.      6826936.69      1580015.93      6826666.21
      1580361.44      6826200.91
#Sta/Elev= 30
  4450.4 1775.06  4500.9 1774.85  4515.3 1774.01  4521.8 1772.32  4536.1 1771.86
  4550.5 1772.82  4556.9 1771.74  4628.8 1770.78  4635.2 1771.74  4678.4 1772.48
  4785.4  1772.2    4835 1770.96  4855.8 1771.82    4914 1772.12  4976.8 1769.56
  4999.5  1769.5  5014.1 1767.19  5017.5 1765.35    5018 1764.85  5035.7 1765.35
    5064 1769.46  5105.9 1769.96  5141.3 1772.91    5156 1773.39  5291.6 1776.51
  5341.6 1775.55    5350 1774.64  5391.7  1775.1  5420.9 1777.98  5458.9  1778.6
#Mann= 3 ,-1 , 0
  4450.4     .05       0  5017.5     .05       0  5035.7     .05       0
Bank Sta=5017.5,5035.7
XS Rating Curve= 0 ,0
Exp/Cntr=0.3,0.1

Type RM Length L Ch R = 1 ,18227   ,180,180,180
BEGIN DESCRIPTION:
Mapping XS e074b4ad
END DESCRIPTION:
XS GIS Cut Line= 3
       1579694.7      6826940.61      1580132.25      6826740.86
       1580665.2       6826501.3
#Sta/Elev= 30
  4386.1 1775.11  4441.4 1774.63  4455.2 1772.67  4472.8 1774.13  4495.8 1774.35
  4518.3 1774.01  4529.8 1772.79  4547.4  1772.8  4552.9 1772.08  4570.4 1773.02
  4575.9 1771.34  4650.5 1770.69  4719.6 1771.71  4771.2 1770.32  4840.2 1771.42
  4909.6 1770.67  4968.8 1769.26  4992.6 1764.58  4993.1 1764.08  5010.8 1764.58
  5036.3 1768.23  5077.2 1769.39  5105.8 1772.47    5129 1773.46  5188.1 1773.46
  5220.9 1771.89  5250.2 1773.26    5302 1774.13  5325.2 1773.67  5451.4 1774.73
#Mann= 3 ,-1 , 0
  4386.1     .05       0  4992.6     .05       0  5010.8     .05       0
Bank Sta=4992.6,5010.8
XS Rating Curve= 0 ,0
Exp/Cntr=0.3,0.1

Type RM Length L Ch R = 1 ,18047   ,285,285,285
BEGIN DESCRIPTION:
Mapping XS 6b04b833
END DESCRIPTION:
XS GIS Cut Line= 4
      1579809.37      6827020.37      1580196.49      6826893.64
      1580635.73      6826721.77      1580785.04      6826628.01
#Sta/Elev= 30
  4431.2 1775.54  4459.2 1774.29  4485.7 1775.15    4491  1773.8  4517.6 1774.31
  4522.9 1773.25  4581.3 1771.91  4586.6 1773.06  4626.5 1771.39    4714 1771.69
  4763.3 1770.87  4784.4 1769.77  4879.9 1770.98  4949.9  1768.8  4978.2 1763.74
  4978.7 1763.24  4996.4 1763.74  5004.2  1766.2  5019.5 1767.84  5094.7 1770.86
  5105.4 1770.83  5118.1 1769.51  5137.2 1771.29  5212.8 1772.02  5256.5 1771.42
  5275.6 1771.91  5298.7 1771.11    5392  1773.5  5436.4 1773.85  5486.5 1772.21
#Mann= 3 ,-1 , 0
  4431.2     .05       0  4978.2     .05       0  4996.4     .05       0
Bank Sta=4978.2,4996.4
XS Rating Curve= 0 ,0
Exp/Cntr=0.3,0.1

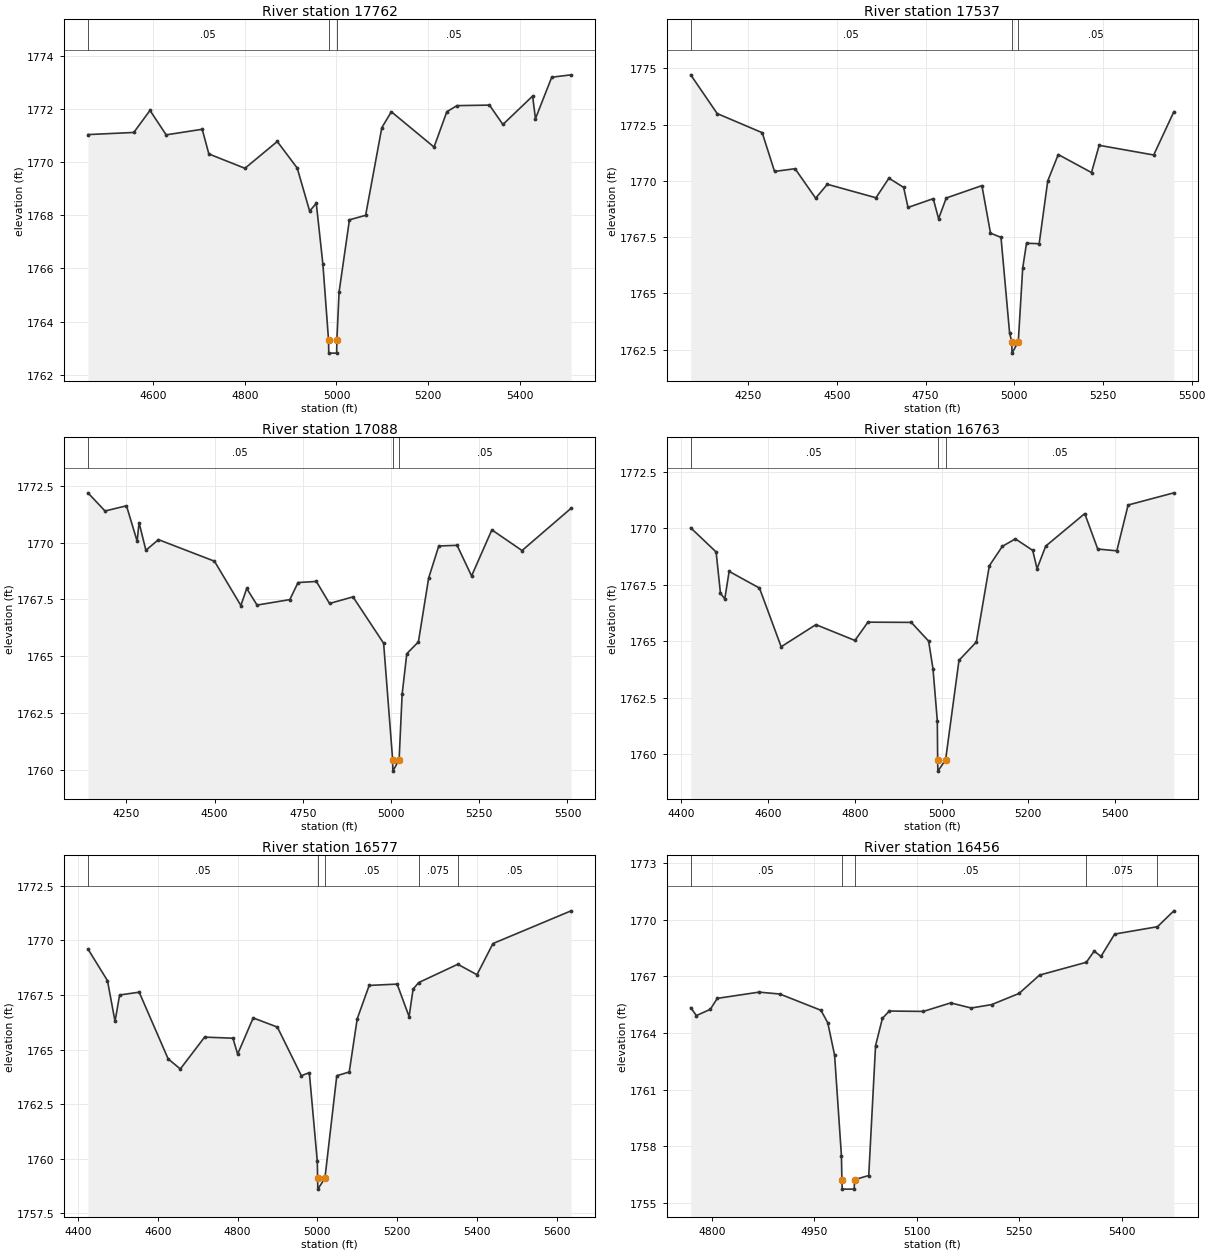
Type RM Length L Ch R = 1 ,17762   ,225,225,225
BEGIN DESCRIPTION:
Mapping XS 36b78d98
END DESCRIPTION:
XS GIS Cut Line= 3
      1580186.05      6827478.74      1580668.71      6826860.66
      1580828.45      6826643.61
#Sta/Elev= 30
    4458 1771.04    4558 1771.12  4593.3 1771.95  4628.6 1771.03  4707.2 1771.24
  4721.7 1770.31  4800.4 1769.77  4870.9 1770.78  4914.4 1769.78  4941.5 1768.16
    4956 1768.45  4970.4 1766.16  4982.7 1763.31  4983.2 1762.81  5000.4 1762.81
  5000.9 1763.31  5005.7 1765.11  5028.3 1767.83  5063.6    1768  5098.9  1771.3
  5119.7  1771.9  5212.8 1770.57  5240.7  1771.9  5262.7 1772.13  5333.7 1772.15
    5363 1771.42  5427.8 1772.49    5434 1771.64  5469.5  1773.2  5511.7 1773.29
#Mann= 3 ,-1 , 0
    4458     .05       0  4982.7     .05       0  5000.9     .05       0
Bank Sta=4982.7,5000.9
XS Rating Curve= 0 ,0
Exp/Cntr=0.3,0.1

Type RM Length L Ch R = 1 ,17537   ,449,449,449
BEGIN DESCRIPTION:
Mapping XS 9d8318c7
END DESCRIPTION:
XS GIS Cut Line= 3
       1580324.9      6827971.89       1580515.5      6827646.53
      1580882.09      6826732.59
#Sta/Elev= 30
    4088 1774.71  4162.6 1772.99  4289.5 1772.14  4324.3 1770.42  4382.2 1770.54
  4440.2 1769.23    4473 1769.85  4610.2 1769.25  4646.7 1770.12  4688.2 1769.71
  4700.5 1768.82  4771.6 1769.21  4786.7 1768.32  4808.3 1769.24  4908.8 1769.79
    4933 1767.68  4962.6 1767.49  4986.8 1763.25  4993.1 1762.85  4993.6 1762.35
  5011.3 1762.85  5023.8 1766.13  5034.5 1767.23  5070.2 1767.21  5094.4    1770
    5124 1771.17  5217.7 1770.37  5239.3 1771.58    5393 1771.15  5449.8 1773.07
#Mann= 3 ,-1 , 0
    4088     .05       0  4993.1     .05       0  5011.3     .05       0
Bank Sta=4993.1,5011.3
XS Rating Curve= 0 ,0
Exp/Cntr=0.3,0.1

Type RM Length L Ch R = 1 ,17088   ,325,325,325
BEGIN DESCRIPTION:
Mapping XS 2d7542a4
END DESCRIPTION:
XS GIS Cut Line= 4
      1580780.65       6828133.3      1580943.84       6827701.8
      1581236.42      6827046.42      1581295.44      6826865.87
#Sta/Elev= 30
  4141.2 1772.19  4189.6 1771.39  4250.4 1771.62  4280.6 1770.06    4286 1770.88
  4305.4 1769.66    4341 1770.13  4499.7 1769.18  4574.5 1767.23  4591.1 1767.98
  4620.4 1767.25  4713.2 1767.49  4736.5 1768.24  4788.4 1768.29  4825.7 1767.32
  4892.2 1767.61    4979 1765.57  5004.6 1760.44  5005.1 1759.94  5022.9 1760.44
  5031.5 1763.33  5044.7 1765.11  5077.6 1765.63  5106.6 1768.44  5135.3 1769.85
  5187.2 1769.88  5228.2 1768.53  5285.7 1770.56  5371.2 1769.65  5510.2 1771.51
#Mann= 3 ,-1 , 0
  4141.2     .05       0  5004.6     .05       0  5022.9     .05       0
Bank Sta=5004.6,5022.9
XS Rating Curve= 0 ,0
Exp/Cntr=0.3,0.1

Type RM Length L Ch R = 1 ,16763   ,186,186,186
BEGIN DESCRIPTION:
Mapping XS 345938bb
END DESCRIPTION:
XS GIS Cut Line= 3
      1581423.87      6827966.62      1581418.25      6827628.12
       1581408.3      6826852.53
#Sta/Elev= 30
  4421.3 1770.03  4479.9 1768.96  4489.9 1767.13  4499.9 1766.88  4509.9  1768.1
  4579.9 1767.36  4629.9 1764.76    4710 1765.74    4800 1765.04    4830 1765.85
    4930 1765.84    4970 1765.01    4980 1763.79    4990 1761.49  4990.8 1759.75
  4991.3 1759.25  5009.1 1759.75    5040 1764.16    5080 1764.97    5110 1768.35
    5140 1769.21    5170 1769.54    5210 1769.03    5220 1768.22    5240 1769.22
    5330 1770.66    5360 1769.09    5404 1769.01    5430 1771.04  5535.5 1771.58
#Mann= 3 ,-1 , 0
  4421.3     .05       0  4990.8     .05       0  5009.1     .05       0
Bank Sta=4990.8,5009.1
XS Rating Curve= 0 ,0
Exp/Cntr=0.3,0.1

Type RM Length L Ch R = 1 ,16577   ,121,121,121
BEGIN DESCRIPTION:
Mapping XS b433ecdf
END DESCRIPTION:
XS GIS Cut Line= 3
      1581528.04      6827956.23       1581604.3       6827505.1
      1581585.22      6826752.28
#Sta/Elev= 30
  4425.2 1769.61  4474.1 1768.16  4493.1 1766.29  4504.5  1767.5  4553.6 1767.63
  4626.2 1764.57  4656.7 1764.11  4717.5 1765.57  4788.5 1765.52  4800.3 1764.79
  4839.2 1766.45  4899.8 1766.03  4959.9  1763.8  4979.9 1763.94  4999.9 1759.87
  5000.7  1759.1  5001.2  1758.6    5019  1759.1  5048.7  1763.8  5079.9 1763.97
  5099.9 1766.41  5129.9 1767.94  5199.9    1768  5229.9 1766.51  5239.9 1767.77
  5253.9 1768.07  5351.9 1768.91    5400 1768.43    5440 1769.86  5635.8 1771.36
#Mann= 5 ,-1 , 0
  4425.2     .05       0  5000.7     .05       0    5019     .05       0
  5253.9    .075       0  5351.9     .05       0
Bank Sta=5000.7,5019
XS Rating Curve= 0 ,0
Exp/Cntr=0.3,0.1

Type RM Length L Ch R = 1 ,16456   ,253,253,253
BEGIN DESCRIPTION:
Mapping XS 54a15205
END DESCRIPTION:
XS GIS Cut Line= 3
      1581750.13       6827616.2      1581724.09      6827480.79
      1581711.98      6826911.31
#Sta/Elev= 30
  4769.1 1765.34  4777.4 1764.92  4797.8 1765.25    4808 1765.83  4869.1 1766.16
  4899.6 1766.06  4959.8  1765.2  4969.8 1764.54  4979.8 1762.83  4989.8 1757.51
  4990.5 1756.24    4991 1755.74  5008.5 1755.74    5009 1756.24  5029.8 1756.46
  5039.8 1763.33  5049.8 1764.77  5059.8 1765.16  5109.8 1765.14  5149.8 1765.59
  5179.8 1765.32  5209.8  1765.5  5249.9 1766.09  5279.9 1767.06  5348.5 1767.74
  5359.9 1768.33  5369.9 1768.05  5389.9 1769.23  5452.6 1769.62  5476.6 1770.46
#Mann= 5 ,-1 , 0
  4769.1     .05       0  4990.5     .03       0    5009     .05       0
  5348.5    .075       0  5452.6     .05       0
Bank Sta=4990.5,5009
XS Rating Curve= 0 ,0
Exp/Cntr=0.3,0.1

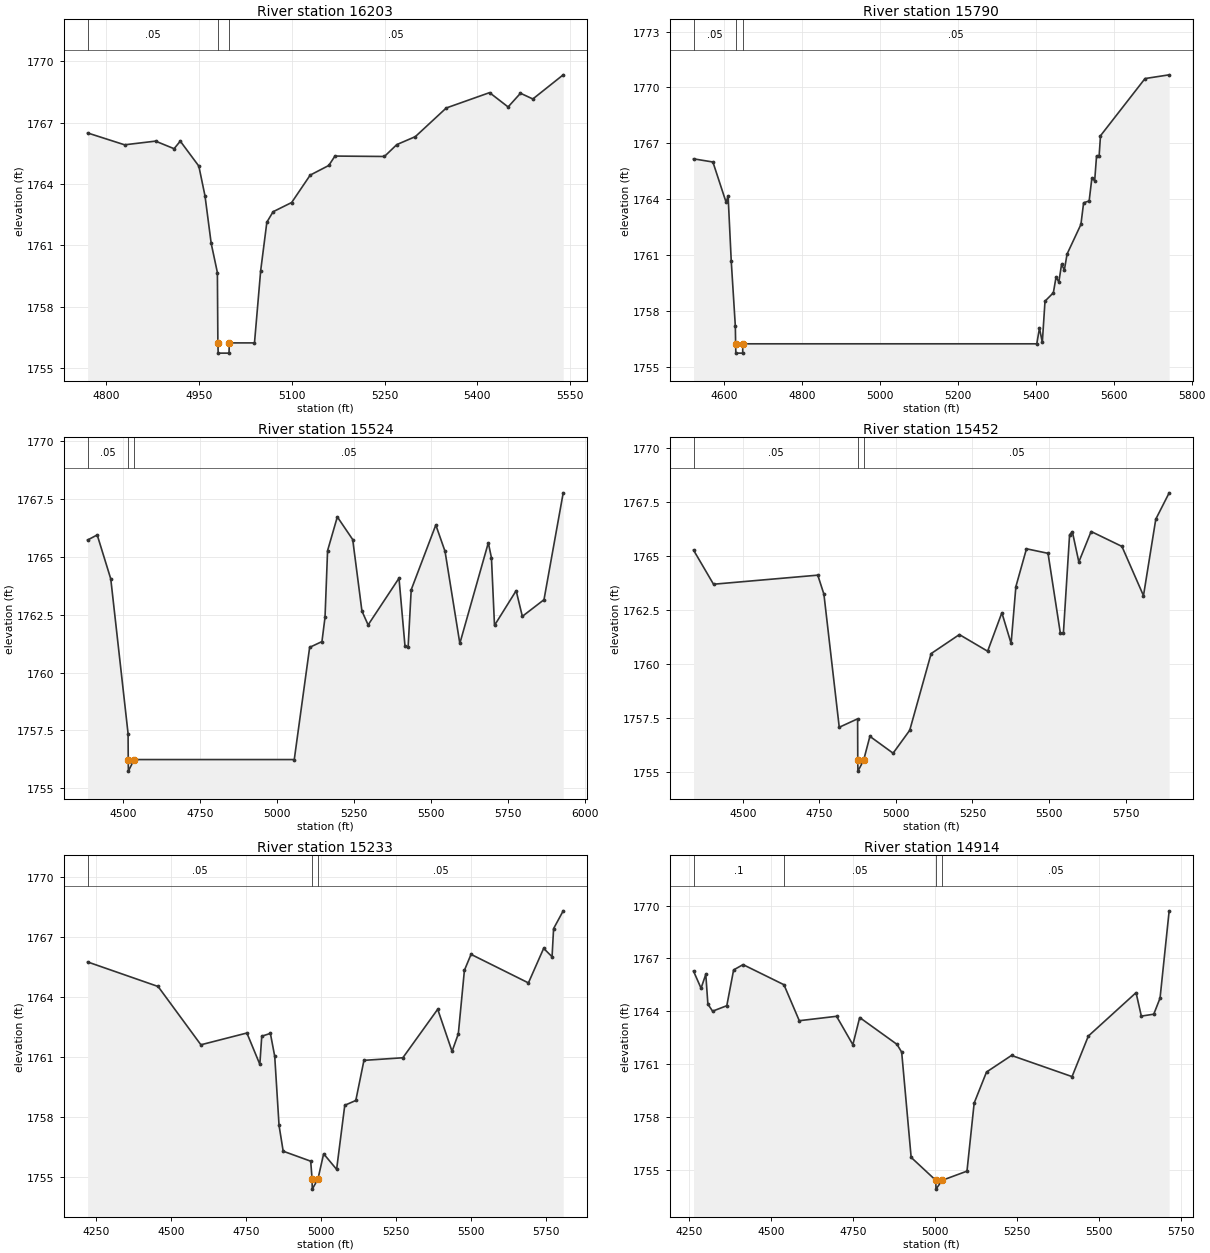
Type RM Length L Ch R = 1 ,16203   ,413,413,413
BEGIN DESCRIPTION:
Mapping XS d0d6a131
END DESCRIPTION:
XS GIS Cut Line= 2
      1581977.57      6827617.94      1581970.62      6826848.87
#Sta/Elev= 30
  4769.7  1766.5  4829.6 1765.92  4879.6  1766.1  4909.6 1765.73  4919.6  1766.1
  4949.6 1764.88  4959.6 1763.42  4969.6  1761.1  4979.6 1759.68  4980.4 1756.24
  4980.9 1755.74  4998.4 1755.74  4998.9 1756.24  5039.6 1756.24  5049.6 1759.77
  5059.6 1762.14  5069.7 1762.65  5099.7  1763.1  5129.7 1764.44  5159.7 1764.91
  5169.7 1765.37  5249.7 1765.35  5269.7 1765.93  5299.7 1766.32  5349.7 1767.72
  5419.7 1768.47  5449.7 1767.77  5469.7 1768.44  5489.7 1768.16  5538.8 1769.34
#Mann= 3 ,-1 , 0
  4769.7     .05       0  4980.4     .05       0  4998.9     .05       0
Bank Sta=4980.4,4998.9
XS Rating Curve= 0 ,0
Exp/Cntr=0.3,0.1

Type RM Length L Ch R = 1 ,15790   ,266,266,266
BEGIN DESCRIPTION:
Mapping XS 2efc6007
END DESCRIPTION:
XS GIS Cut Line= 4
      1581921.97      6827666.57      1582262.29      6827569.34
      1582757.08      6827097.11      1582832.87      6826931.76
#Sta/Elev= 30
  4522.5 1766.17  4572.2    1766    4606 1763.84  4611.2 1764.17  4619.3 1760.66
  4629.7 1757.19  4630.5 1756.24    4631 1755.74  4648.5 1755.74    4649 1756.24
  5402.8 1756.24  5409.7 1757.08    5417 1756.32  5423.9 1758.53  5445.3 1758.98
  5452.2 1759.82  5459.4 1759.56  5466.3  1760.5  5473.6 1760.21  5480.5 1761.06
    5516 1762.65  5522.9 1763.81  5537.1 1763.91    5544 1765.12  5551.3    1765
  5556.1 1766.33  5562.7 1766.33  5566.2 1767.41  5680.4 1770.48  5742.3 1770.68
#Mann= 3 ,-1 , 0
  4522.5     .05       0  4630.5     .03       0    4649     .05       0
Bank Sta=4630.5,4649
XS Rating Curve= 0 ,0
Exp/Cntr=0.3,0.1

Type RM Length L Ch R = 1 ,15524   ,72,72,72
BEGIN DESCRIPTION:
Mapping XS 87e514bf
END DESCRIPTION:
XS GIS Cut Line= 5
      1581923.76      6827689.13      1582133.82      6827671.77
      1582706.73      6827671.77      1583106.04      6827656.14
      1583467.12      6827617.95
#Sta/Elev= 30
  4383.8 1765.73  4415.1 1765.95  4459.2 1764.05  4515.5 1757.36    4516 1756.24
  4516.5 1755.74  4535.1 1756.24  5055.8 1756.24  5105.8 1761.09  5145.8 1761.34
  5155.8 1762.39  5164.1 1765.27  5195.8 1766.73  5245.8 1765.75  5275.8 1762.66
  5295.9 1762.06  5396.3 1764.08  5415.9 1761.13    5426 1761.11    5436 1763.58
    5516 1766.38    5546 1765.24  5594.1 1761.26  5686.7 1765.61  5696.9 1764.96
  5706.8 1762.04  5777.2 1763.54  5797.3 1762.43  5867.7 1763.15  5930.2 1767.77
#Mann= 3 ,-1 , 0
  4383.8     .05       0    4516     .03       0  4535.1     .05       0
Bank Sta=4516,4535.1
XS Rating Curve= 0 ,0
Exp/Cntr=0.3,0.1

Type RM Length L Ch R = 1 ,15452   ,219,219,219
BEGIN DESCRIPTION:
Mapping XS faffaadd
END DESCRIPTION:
XS GIS Cut Line= 4
      1581929.83      6827712.71      1582296.14      6827735.28
      1582780.52      6827714.45      1583478.41       6827639.8
#Sta/Elev= 30
  4338.8 1765.26  4404.1 1763.68  4744.7  1764.1  4764.7 1763.22  4814.8 1757.06
  4874.8 1757.45  4875.3 1755.53  4875.8 1755.03  4894.4 1755.53  4914.9 1756.64
  4990.7 1755.86    5045 1756.92    5115 1760.47  5207.2 1761.35  5299.5 1760.58
    5346 1762.36  5376.2 1760.94  5391.8 1763.57  5426.4 1765.32  5496.8 1765.11
  5537.1 1761.41  5547.1 1761.44  5567.2 1765.97  5576.3 1766.11  5597.4 1764.71
  5637.6 1766.12  5738.2 1765.43  5808.6 1763.15  5848.8 1766.69  5892.5 1767.91
#Mann= 3 ,-1 , 0
  4338.8     .05       0  4875.3     .03       0  4894.4     .05       0
Bank Sta=4875.3,4894.4
XS Rating Curve= 0 ,0
Exp/Cntr=0.3,0.1

Type RM Length L Ch R = 1 ,15233   ,319,319,319
BEGIN DESCRIPTION:
Mapping XS 4510d749
END DESCRIPTION:
XS GIS Cut Line= 4
      1582082.57      6828280.43      1582462.81      6828103.34
       1582895.1      6827757.85      1583499.23      6827646.75
#Sta/Elev= 30
  4221.4 1765.77  4456.7 1764.54  4599.5 1761.62    4753 1762.21  4796.2 1760.64
  4802.6 1762.05  4831.4 1762.19  4845.9 1761.04  4860.3 1757.58  4874.1 1756.29
  4965.9 1755.79  4970.6 1754.89  4971.1 1754.39    4990 1754.89  5009.1 1756.16
  5052.4 1755.38  5079.6 1758.59  5116.4 1758.83  5143.6 1760.84  5273.4 1760.97
  5389.7  1763.4  5437.6 1761.29  5458.5 1762.17  5478.8 1765.35  5500.9 1766.15
  5692.4 1764.72  5743.2 1766.45  5771.3 1766.03  5776.4 1767.44  5808.5 1768.33
#Mann= 3 ,-1 , 0
  4221.4     .05       0  4970.6     .03       0    4990     .05       0
Bank Sta=4970.6,4990
XS Rating Curve= 0 ,0
Exp/Cntr=0.3,0.1

Type RM Length L Ch R = 1 ,14914   ,162,162,162
BEGIN DESCRIPTION:
Mapping XS 92158b0f
END DESCRIPTION:
XS GIS Cut Line= 4
      1582495.77      6828671.08      1583053.09      6827969.65
       1583395.1      6827704.03      1583511.55      6827668.07
#Sta/Elev= 30
  4262.4 1766.28  4285.4 1765.31  4299.8  1766.1  4306.2 1764.41  4320.6 1764.01
  4363.9 1764.32  4384.7 1766.35  4413.5 1766.65  4538.2 1765.51    4585 1763.47
  4698.7 1763.72  4748.4 1762.11  4769.2 1763.65  4882.9 1762.13  4897.3 1761.69
  4926.2 1755.72  5001.4 1754.42  5001.9 1753.92  5020.8 1754.42  5096.5 1754.94
  5118.4  1758.8  5156.1 1760.56  5232.3  1761.5    5417  1760.3  5466.7  1762.6
  5612.2 1765.06  5628.3 1763.73  5666.2 1763.84  5685.4 1764.75  5713.2  1769.7
#Mann= 4 ,-1 , 0
  4262.4      .1       0  4538.2     .05       0  5001.4     .03       0
  5020.8     .05       0
Bank Sta=5001.4,5020.8
XS Rating Curve= 0 ,0
Exp/Cntr=0.3,0.1