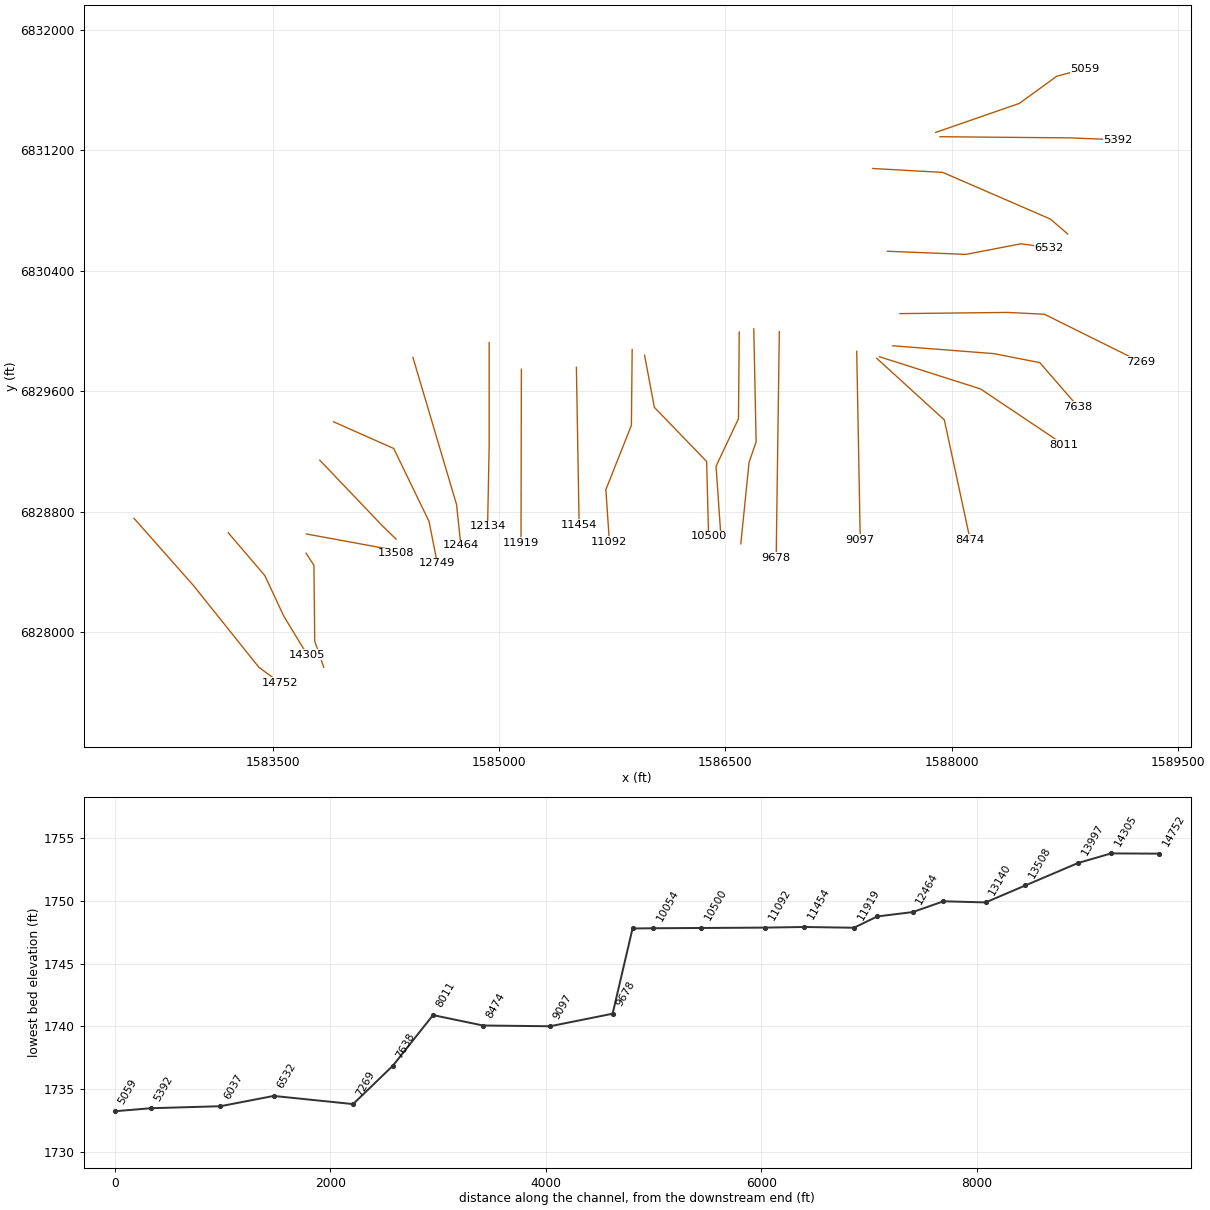
HEC-RAS study Buttonwillow Creek.prj: Buttonwillow Creek Base Level Engineering

--- Buttonwillow Creek.g01 (geometry) --- (continued)

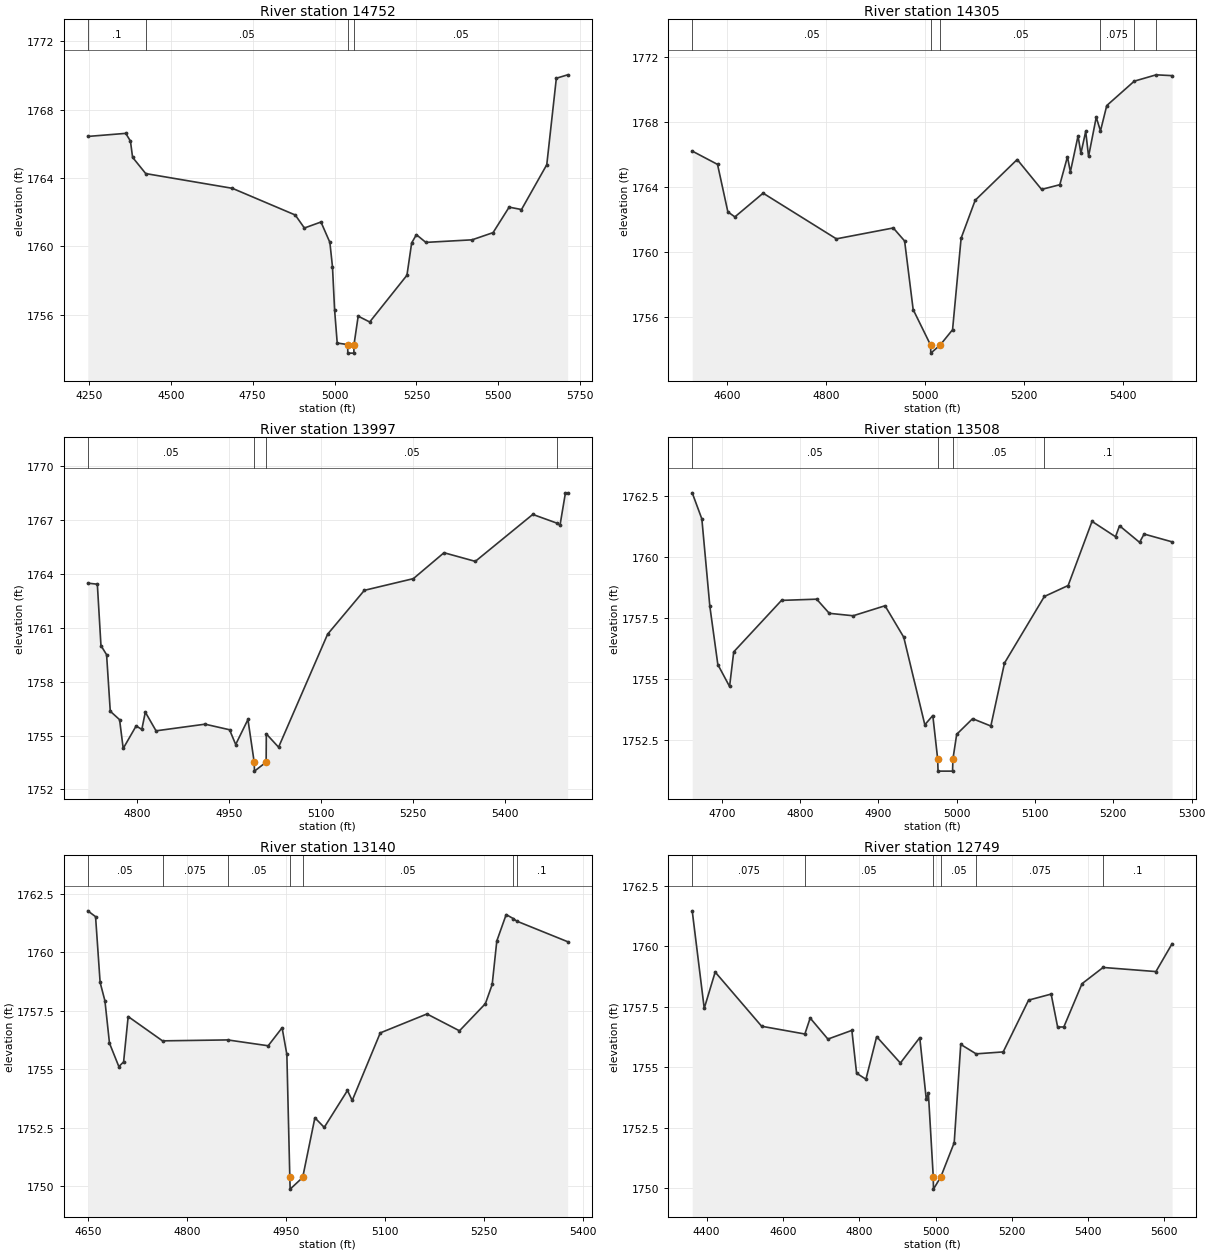
Type RM Length L Ch R = 1 ,14752   ,447,447,447
BEGIN DESCRIPTION:
Mapping XS 6b9aace9
END DESCRIPTION:
XS GIS Cut Line= 4
      1582579.63      6828755.79      1582972.88      6828310.45
      1583407.77      6827766.18      1583547.76      6827662.49
#Sta/Elev= 30
  4246.7 1766.43  4362.6 1766.61  4376.9 1766.16  4383.5 1765.21  4423.6 1764.26
    4688  1763.4  4880.1 1761.84    4908 1761.08  4958.6 1761.43  4985.8 1760.24
  4993.8  1758.8  5000.2  1756.3  5008.2 1754.36  5040.1 1754.27  5040.6 1753.77
    5059 1753.77  5059.5 1754.27  5072.2 1755.93  5107.4 1755.59  5221.1 1758.32
  5235.5 1760.21  5249.9 1760.69  5278.8 1760.24    5420 1760.39    5484 1760.81
  5533.1  1762.3  5570.8 1762.16    5648 1764.78  5677.2 1769.83  5711.7 1770.03
#Mann= 4 ,-1 , 0
  4246.7      .1       0  4423.6     .05       0  5040.1     .03       0
  5059.5     .05       0
Bank Sta=5040.1,5059.5
XS Rating Curve= 0 ,0
Exp/Cntr=0.3,0.1

Type RM Length L Ch R = 1 ,14305   ,308,308,308
BEGIN DESCRIPTION:
Mapping XS 3a87d4d5
END DESCRIPTION:
XS GIS Cut Line= 4
      1583204.62      6828659.44      1583446.84      6828375.56
      1583571.84      6828107.33       1583728.1      6827849.49
#Sta/Elev= 30
  4529.1 1766.22  4580.3  1765.4  4601.2 1762.48  4615.4 1762.17  4672.5 1763.63
  4820.7 1760.82  4935.8 1761.49  4958.7 1760.69    4976 1756.47  5011.2 1754.29
  5011.7 1753.79  5030.7 1754.29  5055.7 1755.23    5073 1760.86  5101.4 1763.19
  5186.4  1765.7  5235.8 1763.86  5272.6 1764.15  5288.1 1765.87    5294 1764.94
  5309.5 1767.15  5315.3 1766.08    5325 1767.43  5330.8 1765.89  5346.3  1768.3
  5354.9 1767.46  5367.6 1769.02  5423.2 1770.52  5467.5 1770.91  5499.7 1770.86
#Mann= 6 ,-1 , 0
  4529.1     .05       0  5011.2     .03       0  5030.7     .05       0
  5354.9    .075       0  5423.2     .05       0  5467.5    .075       0
Bank Sta=5011.2,5030.7
XS Rating Curve= 0 ,0
Exp/Cntr=0.3,0.1

Type RM Length L Ch R = 1 ,13997   ,489,489,489
BEGIN DESCRIPTION:
Mapping XS b5635808
END DESCRIPTION:
XS GIS Cut Line= 4
      1583720.25      6828524.04      1583772.36      6828443.27
      1583777.57      6827940.66      1583837.45      6827766.21
#Sta/Elev= 30
  4719.2 1763.47  4734.8 1763.41  4740.7    1760  4749.9 1759.49  4755.9 1756.35
  4771.1 1755.88    4777 1754.28  4798.1 1755.53  4807.4 1755.34  4813.1  1756.3
  4830.6 1755.26  4910.6 1755.63  4950.6 1755.32  4960.6  1754.5  4980.6 1755.89
  4990.8 1753.52  4991.3 1753.02  5010.3 1753.52  5010.6 1755.09  5030.6 1754.35
  5110.6 1760.63  5170.6 1763.07  5250.6 1763.72  5300.6 1765.16  5351.7 1764.68
  5445.5 1767.29  5485.3  1766.8  5489.9 1766.68  5498.8 1768.49  5502.4 1768.49
#Mann= 4 ,-1 , 0
  4719.2     .05       0  4990.8     .03       0  5010.3     .05       0
  5485.3    .075       0
Bank Sta=4990.8,5010.3
XS Rating Curve= 0 ,0
Exp/Cntr=0.3,0.1

Type RM Length L Ch R = 1 ,13508   ,368,368,368
BEGIN DESCRIPTION:
Mapping XS 30b351c3
END DESCRIPTION:
XS GIS Cut Line= 3
      1583722.88       6828651.6      1584274.96      6828550.04
      1584319.23        6828524.
#Sta/Elev= 30
  4662.3 1762.64  4674.6 1761.57  4684.8 1757.99    4695  1755.6    4710  1754.7
  4715.3 1756.12  4776.3 1758.23  4821.2 1758.28  4837.3  1757.7  4867.8  1757.6
  4908.5 1758.01  4932.4 1756.72  4959.3 1753.13  4969.5 1753.51  4975.7 1751.73
  4976.2 1751.23  4994.7 1751.23  4995.2 1751.73    5000 1752.74  5020.3 1753.38
  5043.6 1753.08    5061 1755.66  5111.9 1758.39  5142.3 1758.84  5172.8 1761.47
  5202.8 1760.84  5207.9 1761.29  5233.5 1760.61  5239.3 1760.95    5275 1760.63
#Mann= 4 ,-1 , 0
  4662.3     .05       0  4975.7     .03       0  4995.2     .05       0
  5111.9      .1       0
Bank Sta=4975.7,4995.2
XS Rating Curve= 0 ,0
Exp/Cntr=0.3,0.1

Type RM Length L Ch R = 1 ,13140   ,391,391,391
BEGIN DESCRIPTION:
Mapping XS 487a3c04
END DESCRIPTION:
XS GIS Cut Line= 3
      1583811.44      6829141.16      1584225.48      6828706.29
      1584316.61      6828617.77
#Sta/Elev= 30
    4649 1761.78  4660.8 1761.53  4667.7 1758.72    4675 1757.93  4681.9 1756.12
  4696.1 1755.12  4703.3 1755.32  4710.2 1757.26  4762.3 1756.22  4861.1 1756.26
  4922.5 1756.01  4943.6 1756.78  4950.8 1755.64  4955.3 1750.38  4955.8 1749.88
  4974.8 1750.38  4993.3 1752.93  5007.5 1752.52  5042.7  1754.1  5049.9 1753.67
  5092.4 1756.56  5163.2 1757.37  5212.5 1756.65  5251.8 1757.81  5262.1 1758.63
  5269.1 1760.49  5283.3 1761.62    5294 1761.45  5299.3 1761.34  5376.5 1760.46
#Mann= 7 ,-1 , 0
    4649     .05       0  4762.3    .075       0  4861.1     .05       0
  4955.3     .03       0  4974.8     .05       0    5294    .075       0
  5299.3      .1       0
Bank Sta=4955.3,4974.8
XS Rating Curve= 0 ,0
Exp/Cntr=0.3,0.1

Type RM Length L Ch R = 1 ,12749   ,285,285,285
BEGIN DESCRIPTION:
Mapping XS 66fb42b1
END DESCRIPTION:
XS GIS Cut Line= 4
      1583902.58      6829396.39        1584301.      6829219.31
      1584535.38      6828734.93      1584590.03      6828456.45
#Sta/Elev= 30
  4362.2 1761.47  4393.7 1757.44  4422.4 1758.94  4544.2  1756.7  4657.5 1756.38
  4671.4 1757.04  4717.9 1756.17  4780.7 1756.53  4793.1 1754.76  4817.6 1754.51
  4845.7 1756.27  4907.9 1755.18  4958.7 1756.23  4975.7 1753.69  4981.3 1753.93
  4994.1 1750.47  4994.6 1749.97  5013.7 1750.47    5049 1751.89  5066.1 1755.95
  5106.4 1755.56  5177.4 1755.64    5244 1757.78  5303.1 1758.03  5320.1 1756.67
  5336.3 1756.67  5384.1 1758.46  5439.3 1759.13  5577.8 1758.96  5620.1 1760.11
#Mann= 6 ,-1 , 0
  4362.2    .075       0  4657.5     .05       0  4994.1     .03       0
  5013.7     .05       0  5106.4    .075       0  5439.3      .1       0
Bank Sta=4994.1,5013.7
XS Rating Curve= 0 ,0
Exp/Cntr=0.3,0.1

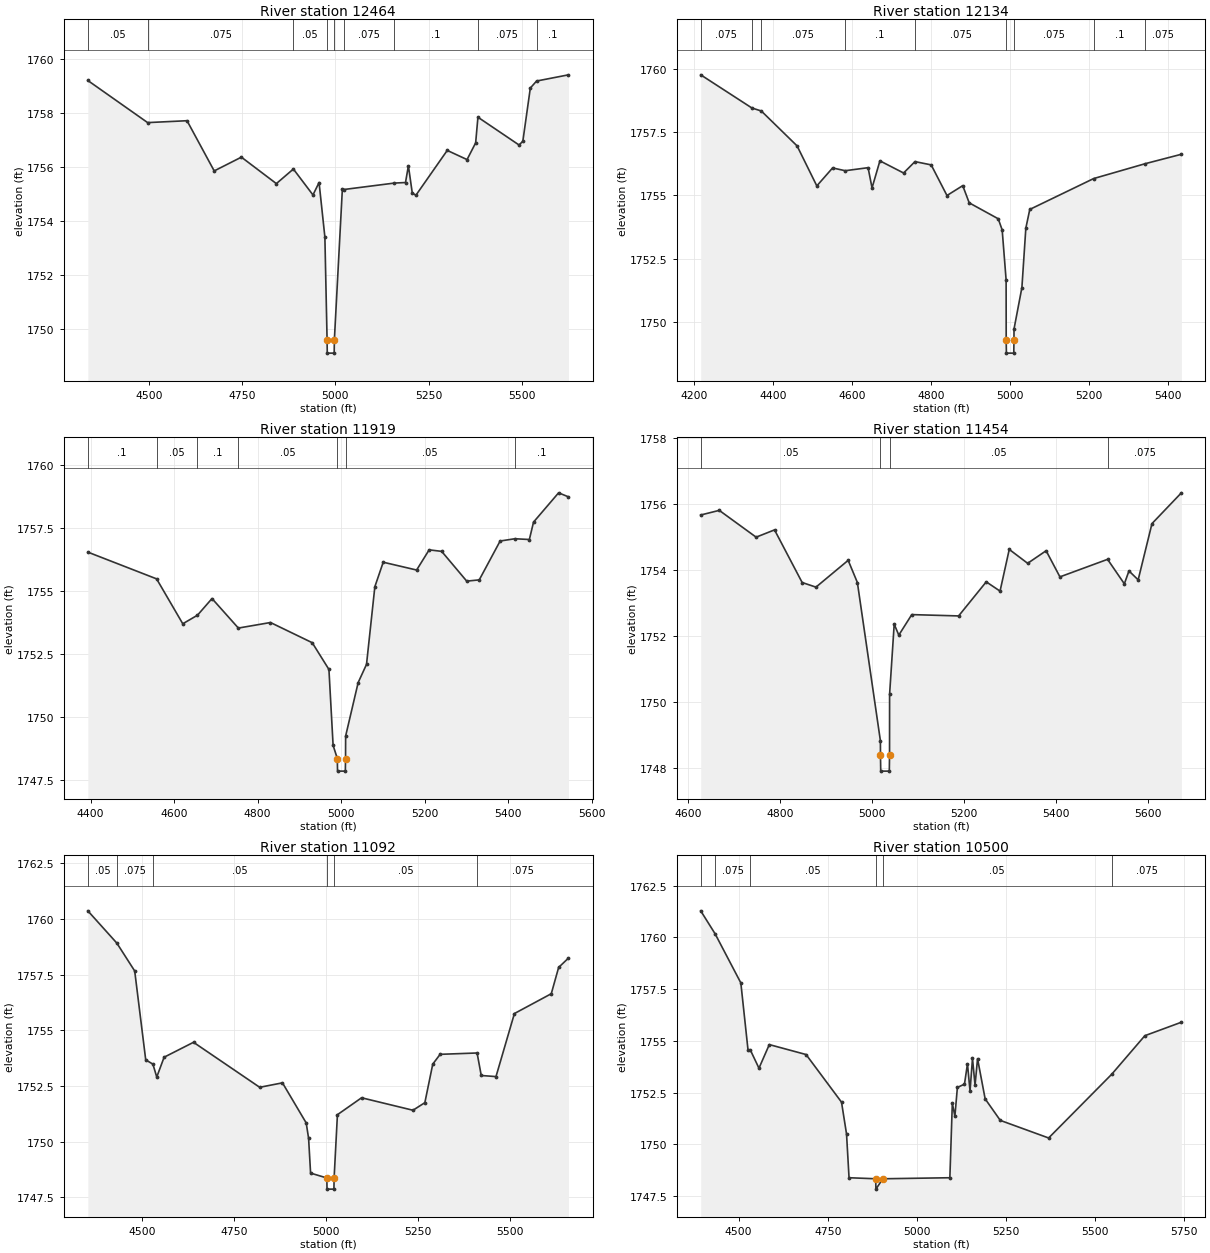
Type RM Length L Ch R = 1 ,12464   ,330,330,330
BEGIN DESCRIPTION:
Mapping XS 2e394a8a
END DESCRIPTION:
XS GIS Cut Line= 3
      1584428.61      6829823.46      1584717.67      6828846.91
      1584746.32      6828576.05
#Sta/Elev= 30
  4335.1 1759.21  4495.7 1757.65  4601.5 1757.72  4674.5 1755.86  4747.5 1756.37
  4841.4 1755.39  4887.1 1755.93  4939.7 1754.97  4956.1 1755.43  4971.7 1753.41
  4977.6 1749.61  4978.1 1749.11  4996.7 1749.11  4997.2 1749.61  5018.7  1755.2
  5021.9 1755.17  5158.3 1755.41  5188.2 1755.43    5196 1756.05  5206.4 1755.04
  5216.2 1754.96  5300.3 1756.62  5353.5 1756.28  5376.6  1756.9  5382.7 1757.85
  5493.2 1756.82  5503.3 1756.96  5523.4 1758.93  5540.2 1759.19  5625.9 1759.42
#Mann= 9 ,-1 , 0
  4335.1     .05       0  4495.7    .075       0  4887.1     .05       0
  4977.6     .03       0  4997.2     .05       0  5021.9    .075       0
  5158.3      .1       0  5382.7    .075       0  5540.2      .1       0
Bank Sta=4977.6,4997.2
XS Rating Curve= 0 ,0
Exp/Cntr=0.3,0.1

Type RM Length L Ch R = 1 ,12134   ,215,215,215
BEGIN DESCRIPTION:
Mapping XS c788af26
END DESCRIPTION:
XS GIS Cut Line= 3
      1584933.82      6829922.42      1584933.82      6829240.14
       1584923.4      6828703.72
#Sta/Elev= 30
  4215.8 1759.76  4345.5 1758.45  4369.5 1758.33  4460.2 1756.95  4510.2 1755.37
  4550.2 1756.08  4582.2 1755.97  4640.2 1756.09  4650.2 1755.29  4670.2 1756.36
  4730.2 1755.88  4759.1 1756.33  4800.2  1756.2  4840.2 1754.99  4880.2 1755.38
  4896.6  1754.7  4970.2 1754.07  4980.2 1753.63  4990.2 1751.65  4990.4 1749.26
  4990.9 1748.76  5009.6 1748.76  5010.1 1749.26  5010.2 1749.71  5030.2 1751.35
  5040.2  1753.7  5050.2 1754.44  5212.2 1755.66  5343.4 1756.25  5434.6 1756.62
#Mann= 9 ,-1 , 0
  4215.8    .075       0  4345.5      .1       0  4369.5    .075       0
  4582.2      .1       0  4759.1    .075       0  4990.4     .07       0
  5010.1    .075       0  5212.2      .1       0  5343.4    .075       0
Bank Sta=4990.4,5010.1
XS Rating Curve= 0 ,0
Exp/Cntr=0.3,0.1

Type RM Length L Ch R = 1 ,11919   ,465,465,465
BEGIN DESCRIPTION:
Mapping XS c34731e7
END DESCRIPTION:
XS GIS Cut Line= 2
      1585147.36       6829745.4      1585144.75       6828594.3
#Sta/Elev= 30
  4393.5 1756.54  4558.2 1755.48  4620.9  1753.7  4656.1 1754.04  4690.9  1754.7
    4754 1753.53  4830.9 1753.75  4930.9 1752.95  4970.9 1751.89  4980.9 1748.88
    4991 1748.36  4991.5 1747.86  5010.2 1747.86  5010.7 1748.36  5010.9 1749.25
  5040.9 1751.37  5060.9 1752.09  5080.9 1755.17  5100.9 1756.14  5180.9 1755.83
  5210.9 1756.63  5240.9 1756.57  5300.9 1755.39  5330.9 1755.44  5380.9 1756.98
  5416.1 1757.07  5450.9 1757.04  5460.9 1757.73  5520.9 1758.89  5544.6 1758.73
#Mann= 7 ,-1 , 0
  4393.5      .1       0  4558.2     .05       0  4656.1      .1       0
    4754     .05       0    4991     .07       0  5010.7     .05       0
  5416.1      .1       0
Bank Sta=4991,5010.7
XS Rating Curve= 0 ,0
Exp/Cntr=0.3,0.1

Type RM Length L Ch R = 1 ,11454   ,362,362,362
BEGIN DESCRIPTION:
Mapping XS ba0a7ea9
END DESCRIPTION:
XS GIS Cut Line= 2
      1585511.94      6829758.34      1585530.17       6828714.1
#Sta/Elev= 30
  4628.2 1755.66  4668.5  1755.8  4748.6 1754.99  4788.6 1755.21  4848.6 1753.62
  4878.6 1753.48  4948.6 1754.29  4968.6 1753.62  5018.6 1748.84  5018.8 1748.42
  5019.3 1747.92    5038 1747.92  5038.5 1748.42  5038.6 1750.24  5048.6 1752.36
  5058.6 1752.03  5086.8 1752.65  5188.6 1752.61  5248.6 1753.64  5278.6 1753.36
  5298.6 1754.62  5338.6  1754.2  5378.7 1754.58  5408.7 1753.79  5512.2 1754.32
  5548.7 1753.58  5558.7 1753.97  5578.7  1753.7  5608.7  1755.4  5672.6 1756.33
#Mann= 4 ,-1 , 0
  4628.2     .05       0  5018.8     .03       0  5038.5     .05       0
  5512.2    .075       0
Bank Sta=5018.8,5038.5
XS Rating Curve= 0 ,0
Exp/Cntr=0.3,0.1

Type RM Length L Ch R = 1 ,11092   ,592,592,592
BEGIN DESCRIPTION:
Mapping XS 43acea3a
END DESCRIPTION:
XS GIS Cut Line= 4
      1585881.73      6829875.52      1585876.52      6829372.95
      1585707.25      6828945.87      1585730.57      6828601.26
#Sta/Elev= 30
  4352.5 1760.36  4431.5 1758.91    4480 1757.66    4510 1753.67  4529.5 1753.48
    4540  1752.9    4560 1753.79    4640 1754.46    4820 1752.44  4881.9 1752.64
  4946.5 1750.84    4953 1750.15  4958.4 1748.59  5002.6 1748.37  5003.1 1747.87
  5021.9 1747.87  5022.4 1748.37  5031.4 1751.21  5097.1 1751.97  5236.9 1751.41
  5269.2 1751.75  5290.7 1753.48  5310.8 1753.92  5411.3 1753.98  5422.6 1752.97
  5462.7 1752.92  5512.8 1755.75  5613.1 1756.64  5633.1 1757.82  5659.9 1758.24
#Mann= 6 ,-1 , 0
  4352.5     .05       0  4431.5    .075       0  4529.5     .05       0
  5002.6     .03       0  5022.4     .05       0  5411.3    .075       0
Bank Sta=5002.6,5022.4
XS Rating Curve= 0 ,0
Exp/Cntr=0.3,0.1

Type RM Length L Ch R = 1 ,10500   ,446,446,446
BEGIN DESCRIPTION:
Mapping XS c1de6199
END DESCRIPTION:
XS GIS Cut Line= 4
      1585963.77      6829838.65      1586028.87      6829492.31
      1586375.22      6829132.94      1586388.24      6828635.52
#Sta/Elev= 30
  4393.6 1761.28    4434 1760.17  4506.2  1757.8  4526.5 1754.54  4533.1 1754.55
  4557.1 1753.68  4586.1 1754.82  4689.3 1754.34  4788.8 1752.04  4802.9  1750.5
  4809.9 1748.39  4884.8 1748.34  4885.3 1747.84  4904.7 1748.34  5092.9 1748.39
  5099.8 1751.99    5107 1751.36    5114 1752.75  5133.9 1752.91  5142.3 1753.89
  5149.5 1752.58  5156.4 1754.15  5163.6 1752.86  5170.6 1754.14  5191.9  1752.2
  5234.4 1751.16  5370.1 1750.31  5547.3 1753.39  5640.2 1755.25  5742.7  1755.9
#Mann= 6 ,-1 , 0
  4393.6     .05       0    4434    .075       0  4533.1     .05       0
  4884.8     .03       0  4904.7     .05       0  5547.3    .075       0
Bank Sta=4884.8,4904.7
XS Rating Curve= 0 ,0
Exp/Cntr=0.3,0.1

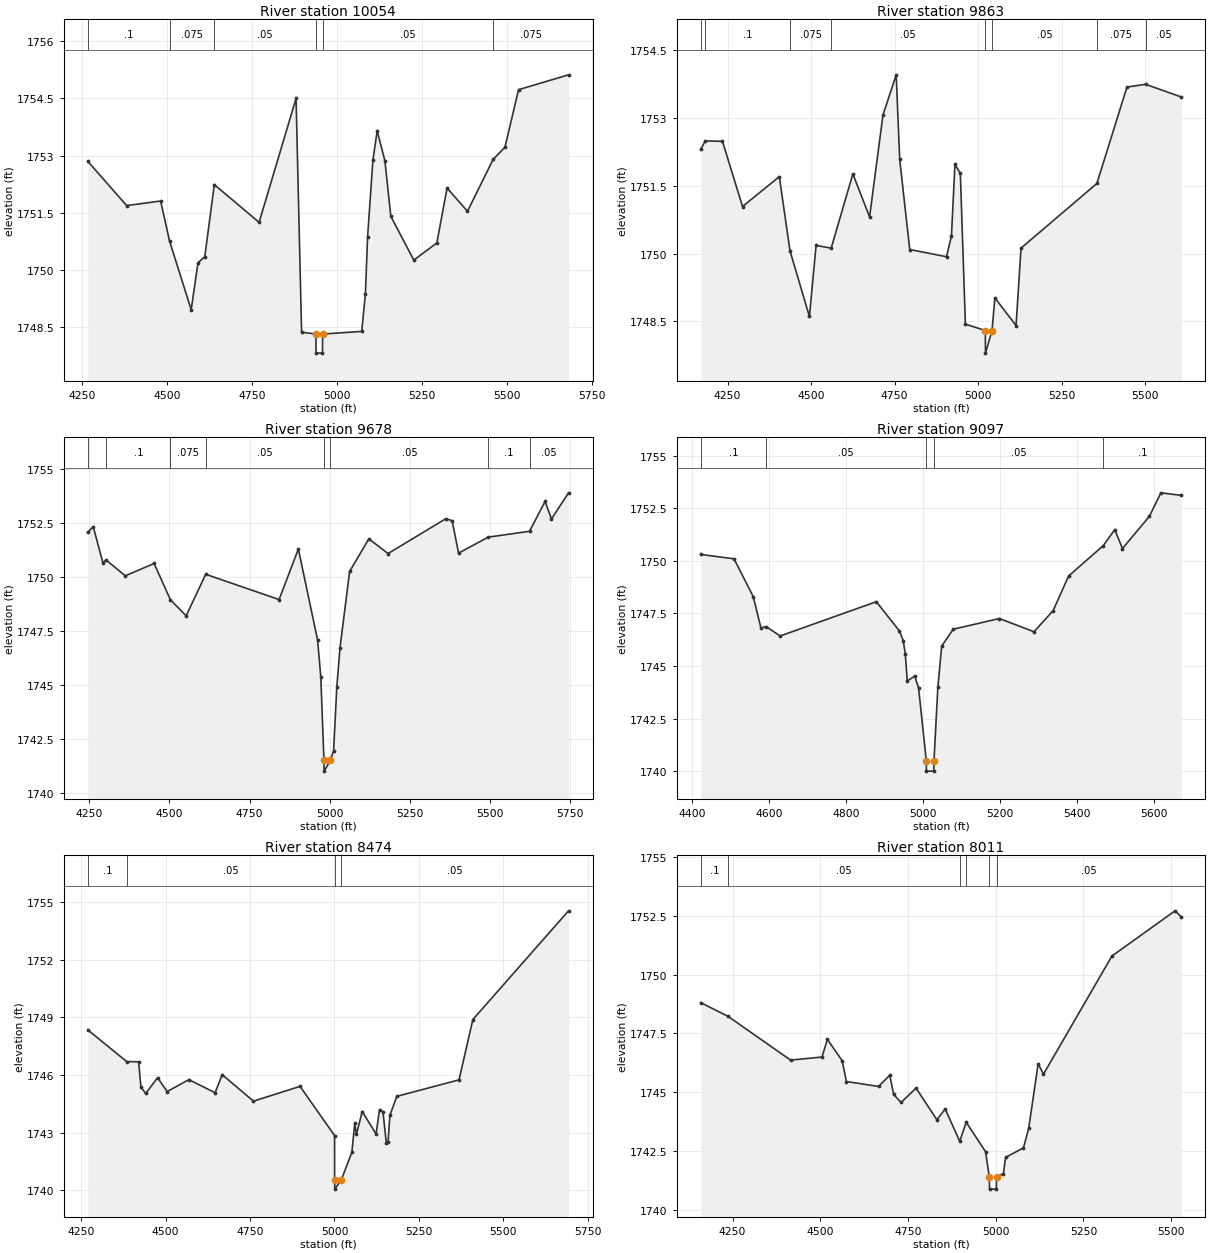
Type RM Length L Ch R = 1 ,10054   ,191,191,191
BEGIN DESCRIPTION:
Mapping XS d9c1a917
END DESCRIPTION:
XS GIS Cut Line= 4
      1586591.37      6829992.35      1586586.16      6829416.79
      1586437.72      6829101.69      1586471.46      6828611.24
#Sta/Elev= 30
  4266.5 1752.85  4380.9 1751.69  4480.9 1751.81  4507.1 1750.76  4570.9 1748.96
  4590.9 1750.19  4610.9 1750.35    4639 1752.24  4770.9 1751.25  4879.7  1754.5
    4896 1748.37  4938.1 1748.32  4938.6 1747.82  4957.5 1747.82    4958 1748.32
  5073.1 1748.39  5083.9 1749.37  5090.3 1750.86    5106 1752.88  5118.6 1753.65
  5141.4 1752.86  5158.7 1751.41  5226.4 1750.26  5294.3 1750.71  5324.4 1752.15
  5384.5 1751.54  5459.9  1752.9  5494.8 1753.22  5534.9 1754.73    5682 1755.12
#Mann= 6 ,-1 , 0
  4266.5      .1       0  4507.1    .075       0    4639     .05       0
  4938.1     .03       0    4958     .05       0  5459.9    .075       0
Bank Sta=4938.1,4958
XS Rating Curve= 0 ,0
Exp/Cntr=0.3,0.1

Type RM Length L Ch R = 1 ,9863    ,185,185,185
BEGIN DESCRIPTION:
Mapping XS 193d7726
END DESCRIPTION:
XS GIS Cut Line= 4
      1586687.72      6830013.12      1586703.35      6829263.14
      1586656.47      6829127.73      1586601.78      6828586.02
#Sta/Elev= 30
  4169.8  1752.3  4183.4 1752.49  4234.9 1752.48  4294.9 1751.04    4405  1751.7
  4436.9 1750.06    4495 1748.61    4515 1750.18  4560.2 1750.12    4625 1751.76
    4675 1750.81    4715 1753.06  4754.6 1753.95  4765.1 1752.08  4795.1 1750.09
  4905.1 1749.93  4919.9 1750.39  4930.4 1751.97  4946.5 1751.77  4961.6 1748.44
  5021.2  1748.3  5021.7  1747.8  5041.3  1748.3  5049.8 1749.02  5113.2 1748.41
    5128 1750.12    5355 1751.55  5444.9 1753.68  5500.6 1753.74  5607.7 1753.46
#Mann= 8 ,-1 , 0
  4169.8    .075       0  4183.4      .1       0  4436.9    .075       0
  4560.2     .05       0  5021.2     .03       0  5041.3     .05       0
    5355    .075       0  5500.6     .05       0
Bank Sta=5021.2,5041.3
XS Rating Curve= 0 ,0
Exp/Cntr=0.3,0.1

Type RM Length L Ch R = 1 ,9678    ,581,581,581
BEGIN DESCRIPTION:
Mapping XS 57e10cbd
END DESCRIPTION:
XS GIS Cut Line= 2
      1586856.99      6829994.89      1586836.16      6828494.94
#Sta/Elev= 30
  4245.3 1752.06  4262.2 1752.31  4292.2 1750.65  4302.5 1750.77  4362.2 1750.04
  4452.2 1750.61  4502.9 1748.93  4552.2 1748.19  4613.2 1750.11  4842.3 1748.94
  4902.3 1751.28  4962.3 1747.07  4972.3 1745.37  4982.2  1741.5  4982.7    1741
  5002.3  1741.5  5012.3 1741.94  5022.3 1744.88  5032.3 1746.71  5062.3 1750.24
  5122.3 1751.75  5182.3 1751.07  5362.3 1752.68  5382.3 1752.59  5402.3 1751.09
    5495 1751.83  5623.7  1752.1  5672.3 1753.48  5692.3 1752.67  5745.4 1753.88
#Mann= 8 ,-1 , 0
  4245.3    .075       0  4302.5      .1       0  4502.9    .075       0
  4613.2     .05       0  4982.2     .03       0  5002.3     .05       0
    5495      .1       0  5623.7     .05       0
Bank Sta=4982.2,5002.3
XS Rating Curve= 0 ,0
Exp/Cntr=0.3,0.1

Type RM Length L Ch R = 1 ,9097    ,623,623,623
BEGIN DESCRIPTION:
Mapping XS 61db16a8
END DESCRIPTION:
XS GIS Cut Line= 2
      1587370.01      6829864.67      1587393.45      6828614.69
#Sta/Elev= 30
    4422 1750.31  4508.7  1750.1  4558.7  1748.3  4578.7 1746.81  4591.8 1746.88
  4628.7 1746.43  4878.8 1748.06  4938.8 1746.67  4948.8 1746.21  4954.2 1745.56
  4959.2 1744.29  4978.8 1744.52  4988.8 1743.94  5008.7  1740.5  5009.2    1740
  5028.3    1740  5028.8  1740.5  5038.8 1743.98  5048.8 1745.95  5078.8 1746.75
  5198.8 1747.26  5288.8 1746.63  5338.8 1747.64  5378.8 1749.28  5469.2 1750.73
  5498.9 1751.49  5518.9 1750.59  5588.9 1752.12  5618.9 1753.24  5672.2 1753.12
#Mann= 5 ,-1 , 0
    4422      .1       0  4591.8     .05       0  5008.7     .04       0
  5028.8     .05       0  5469.2      .1       0
Bank Sta=5008.7,5028.8
XS Rating Curve= 0 ,0
Exp/Cntr=0.3,0.1

Type RM Length L Ch R = 1 ,8474    ,463,463,463
BEGIN DESCRIPTION:
Mapping XS 420ad8fb
END DESCRIPTION:
XS GIS Cut Line= 3
       1587502.8      6829817.86      1587950.74      6829408.98
      1588122.25       6828611.2
#Sta/Elev= 30
  4270.1 1748.35  4385.1  1746.7  4420.4 1746.69  4427.2 1745.37  4441.4 1745.04
  4476.5 1745.86  4504.9 1745.14  4569.1 1745.76  4646.8 1745.08  4667.7 1746.02
  4760.3 1744.64  4898.1 1745.41  5000.3 1742.85  5000.4 1740.56  5000.9 1740.06
  5020.7 1740.56  5051.5 1741.98    5060 1743.48  5065.1 1742.93  5082.2  1744.1
  5123.1 1742.93  5133.3  1744.2  5143.5 1744.08  5153.6 1742.45  5158.7 1742.53
    5164  1743.9  5184.5 1744.89  5368.6 1745.75  5409.5 1748.89  5692.6 1754.55
#Mann= 4 ,-1 , 0
  4270.1      .1       0  4385.1     .05       0  5000.4     .05       0
  5020.7     .05       0
Bank Sta=5000.4,5020.7
XS Rating Curve= 0 ,0
Exp/Cntr=0.3,0.1

Type RM Length L Ch R = 1 ,8011    ,373,373,373
BEGIN DESCRIPTION:
Mapping XS 5e2f491a
END DESCRIPTION:
XS GIS Cut Line= 3
      1587521.04      6829828.25      1588190.33      6829614.71
      1588744.49      6829242.66
#Sta/Elev= 30
  4159.1 1748.81  4236.9 1748.23  4415.2 1746.37  4504.9  1746.5  4520.1 1747.25
  4562.1 1746.35  4574.5 1745.46  4665.9 1745.25    4698 1745.73  4709.1 1744.91
  4730.1 1744.57  4772.9 1745.18  4832.1 1743.84    4856 1744.29  4897.4 1742.92
  4915.8 1743.73    4971 1742.48  4981.8 1741.39  4982.3 1740.89  5001.7 1740.89
  5002.2 1741.39    5022 1741.55    5028 1742.24    5079 1742.64    5094 1743.48
    5121 1746.22    5136 1745.77  5331.1 1750.79  5511.1 1752.71  5529.1 1752.45
#Mann= 6 ,-1 , 0
  4159.1      .1       0  4236.9     .05       0  4897.4     .12       0
  4915.8     .05       0  4981.8     .05       0  5002.2     .05       0
Bank Sta=4981.8,5002.2
XS Rating Curve= 0 ,0
Exp/Cntr=0.3,0.1

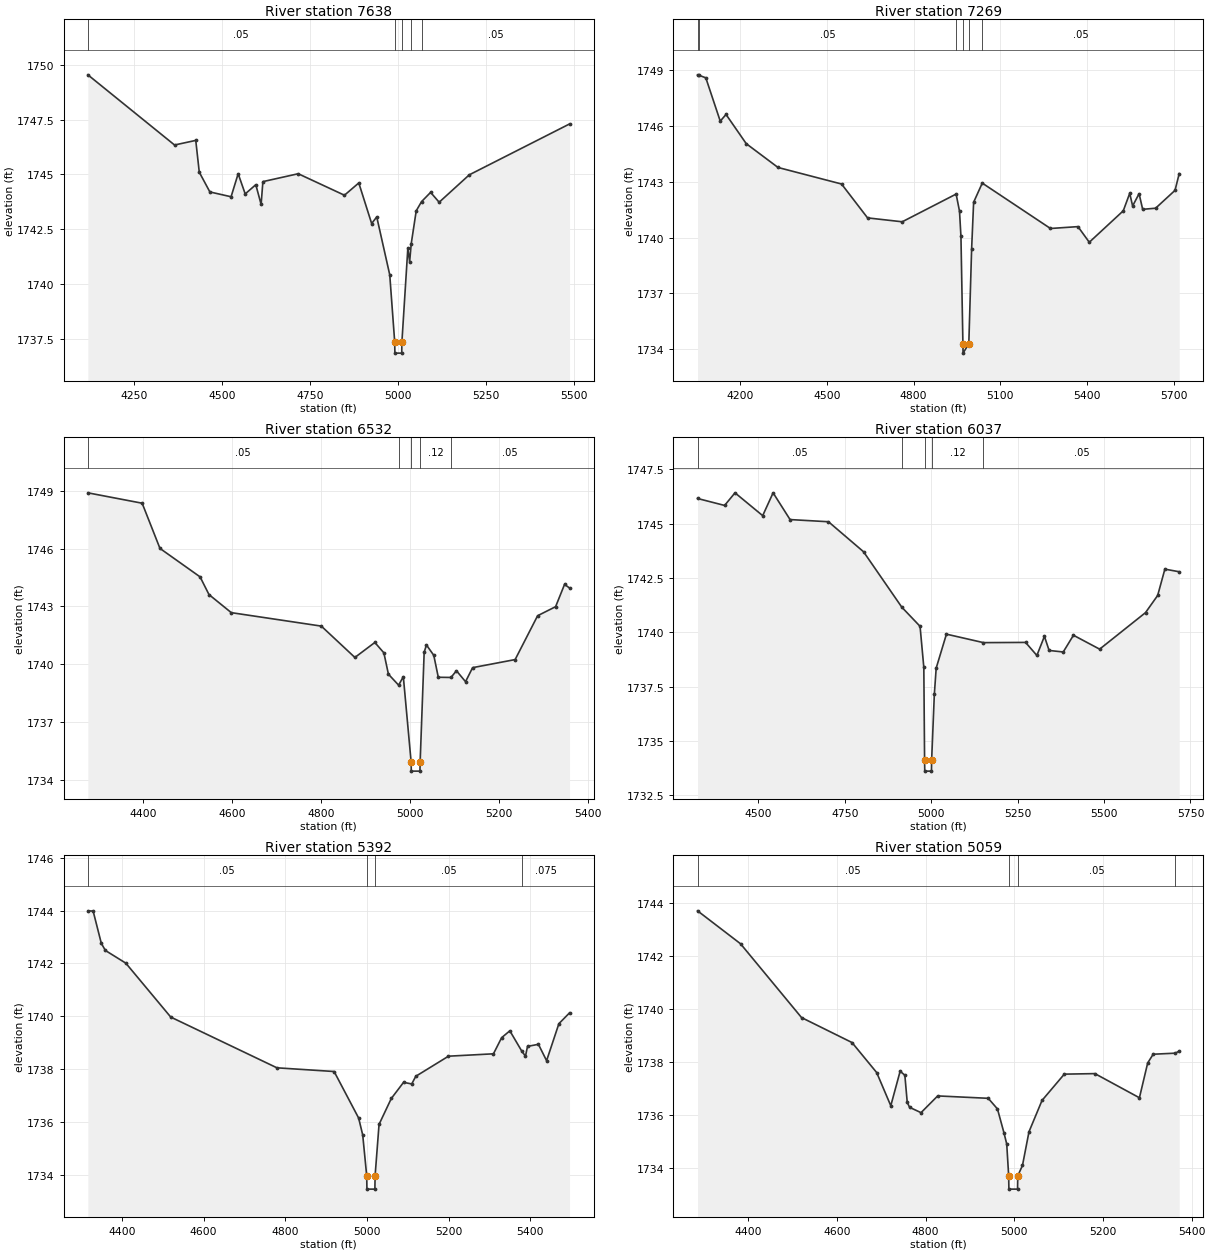
Type RM Length L Ch R = 1 ,7638    ,369,369,369
BEGIN DESCRIPTION:
Mapping XS 6aa75506
END DESCRIPTION:
XS GIS Cut Line= 4
      1587609.62      6829901.16      1588278.87      6829849.08
      1588583.56      6829789.19      1588836.13      6829497.55
#Sta/Elev= 30
    4120 1749.54  4366.1 1746.34  4426.3 1746.55  4436.3  1745.1  4466.4  1744.2
  4526.6 1743.98  4546.7 1745.03  4566.7 1744.11  4596.8 1744.53  4611.9 1743.63
  4616.9 1744.67  4717.2 1745.03  4848.5 1744.05  4889.2 1744.61  4925.7 1742.76
  4940.2 1743.06  4977.1 1740.42  4991.2 1737.35  4991.7 1736.85  5011.1 1736.85
  5011.6 1737.35  5028.5 1741.64  5033.6 1741.02  5038.1 1741.84  5052.3 1743.34
  5067.5 1743.76  5093.1 1744.18  5117.4 1743.73  5202.9 1744.98  5487.6  1747.3
#Mann= 5 ,-1 , 0
    4120     .05       0  4991.2     .04       0  5011.6     .05       0
  5038.1     .12       0  5067.5     .05       0
Bank Sta=4991.2,5011.6
XS Rating Curve= 0 ,0
Exp/Cntr=0.3,0.1

Type RM Length L Ch R = 1 ,7269    ,737,737,737
BEGIN DESCRIPTION:
Mapping XS 62c1203c
END DESCRIPTION:
XS GIS Cut Line= 4
      1587656.43      6830114.71      1588370.01      6830122.52
      1588613.89      6830110.68      1589249.41      6829794.77
#Sta/Elev= 30
    4052 1748.75  4056.2 1748.73  4080.6 1748.59  4130.6 1746.26  4150.6 1746.62
  4220.6 1745.05  4330.6 1743.77  4550.6 1742.88  4640.6 1741.06  4760.6 1740.85
  4947.2 1742.34  4958.9 1741.42  4963.9 1740.06  4970.7 1734.29  4971.2 1733.79
  4991.1 1734.29  5000.9 1739.41  5007.8  1741.9  5037.7 1742.93  5273.8 1740.49
    5369 1740.59  5408.2 1739.75  5525.8 1741.44  5548.2 1742.38  5558.2  1741.7
  5580.6 1742.36    5593 1741.52  5637.8 1741.58    5705 1742.54  5719.5 1743.44
#Mann= 6 ,-1 , 0
    4052    .075       0  4056.2     .05       0  4947.2     .12       0
  4970.7     .06       0  4991.1     .12       0  5037.7     .05       0
Bank Sta=4970.7,4991.1
XS Rating Curve= 0 ,0
Exp/Cntr=0.3,0.1

Type RM Length L Ch R = 1 ,6532    ,495,495,495
BEGIN DESCRIPTION:
Mapping XS 10f6f6a5
END DESCRIPTION:
XS GIS Cut Line= 4
      1587573.18      6830528.77      1588093.97      6830507.94
      1588458.56      6830578.25      1588646.05      6830552.21
#Sta/Elev= 30
  4275.9 1748.91  4397.8 1748.37  4437.8 1746.02  4527.9 1744.54  4547.9 1743.62
    4598 1742.68  4800.2 1741.98  4875.6 1740.35  4920.4 1741.13  4940.7 1740.59
  4950.9 1739.48  4973.8 1738.91  4984.4 1739.35  5001.8 1734.94  5002.3 1734.44
  5021.7 1734.44  5022.2 1734.94  5031.2 1740.62  5036.3    1741  5052.8 1740.46
  5062.9 1739.32  5091.4 1739.31  5103.7 1739.66  5124.1 1739.09    5140 1739.82
  5235.5 1740.24    5286 1742.52  5326.4 1742.99  5346.5 1744.15  5357.7 1743.96
#Mann= 5 ,-1 , 0
  4275.9     .05       0  4973.8     .12       0  5001.8     .07       0
  5022.2     .12       0  5091.4     .05       0
Bank Sta=5001.8,5022.2
XS Rating Curve= 0 ,0
Exp/Cntr=0.3,0.1

Type RM Length L Ch R = 1 ,6037    ,645,645,645
BEGIN DESCRIPTION:
Mapping XS 61606178
END DESCRIPTION:
XS GIS Cut Line= 4
      1587476.79      6831078.25      1587940.33      6831052.21
      1588653.87      6830742.31      1588768.45      6830643.35
#Sta/Elev= 30
  4323.9 1746.16  4402.2 1745.84  4432.3 1746.42  4512.4 1745.37  4542.5 1746.42
  4591.6 1745.19  4702.7 1745.09  4804.2 1743.71  4914.9 1741.16  4967.7 1740.28
  4978.6 1738.39  4980.8 1734.12  4981.3 1733.62  5000.7 1733.62  5001.2 1734.12
    5009 1737.15  5014.4 1738.36    5044 1739.92  5151.2 1739.53    5273 1739.54
  5305.7 1738.94  5327.5 1739.82  5341.1 1739.17    5382  1739.1  5411.5 1739.87
  5487.3 1739.23    5620 1740.91  5655.2  1741.7    5676 1742.91  5717.5 1742.79
#Mann= 5 ,-1 , 0
  4323.9     .05       0  4914.9     .12       0  4980.8     .07       0
  5001.2     .12       0  5151.2     .05       0
Bank Sta=4980.8,5001.2
XS Rating Curve= 0 ,0
Exp/Cntr=0.3,0.1

Type RM Length L Ch R = 1 ,5392    ,333,333,333
BEGIN DESCRIPTION:
Mapping XS 96472b9e
END DESCRIPTION:
XS GIS Cut Line= 3
      1587922.11      6831289.19      1588789.28      6831281.37
      1589101.12      6831268.78
#Sta/Elev= 30
  4316.7 1743.99  4329.6 1743.98  4349.6 1742.76  4359.6 1742.49  4409.6 1742.01
  4519.6 1739.97  4779.6 1738.05  4919.6 1737.91  4979.6 1736.15  4989.6 1735.51
  4999.4 1733.96  4999.9 1733.46  5019.4 1733.46  5019.9 1733.96  5029.6 1735.91
  5059.6 1736.89  5089.6  1737.5  5109.6 1737.44  5119.6 1737.73  5199.6 1738.49
  5309.7 1738.58  5329.7 1739.19  5349.8 1739.45  5379.1 1738.68  5388.1 1738.49
  5393.1 1738.86  5419.8 1738.94  5439.8 1738.32  5469.9 1739.72    5496 1740.13
#Mann= 4 ,-1 , 0
  4316.7     .05       0  4999.4     .03       0  5019.9     .05       0
  5379.1    .075       0
Bank Sta=4999.4,5019.9
XS Rating Curve= 0 ,0
Exp/Cntr=0.3,0.1

Type RM Length L Ch R = 1 ,5059    ,370,370,370
BEGIN DESCRIPTION:
Mapping XS 265b04e7
END DESCRIPTION:
XS GIS Cut Line= 4
      1587893.45      6831317.83      1588448.14      6831510.54
      1588695.99      6831691.01      1588881.71      6831740.48
#Sta/Elev= 30
    4286  1743.7  4382.9 1742.46  4520.5 1739.68  4634.3 1738.74  4689.9 1737.61
  4721.7 1736.36  4742.8 1737.66  4753.4 1737.51  4758.8 1736.49  4764.1  1736.3
  4789.9  1736.1  4827.5 1736.73  4941.4 1736.64  4962.2 1736.24  4976.9 1735.34
  4983.1 1734.92  4987.5 1733.72    4988 1733.22  5007.5 1733.22    5008 1733.72
  5018.6 1734.11  5033.3 1735.38  5062.7 1736.56  5112.9 1737.55  5181.9 1737.57
  5282.3 1736.66  5300.9 1737.97  5313.3  1738.3  5363.5 1738.34    5372 1738.42
#Mann= 4 ,-1 , 0
    4286     .05       0  4987.5     .03       0    5008     .05       0
  5363.5     .12       0
Bank Sta=4987.5,5008
XS Rating Curve= 0 ,0
Exp/Cntr=0.3,0.1