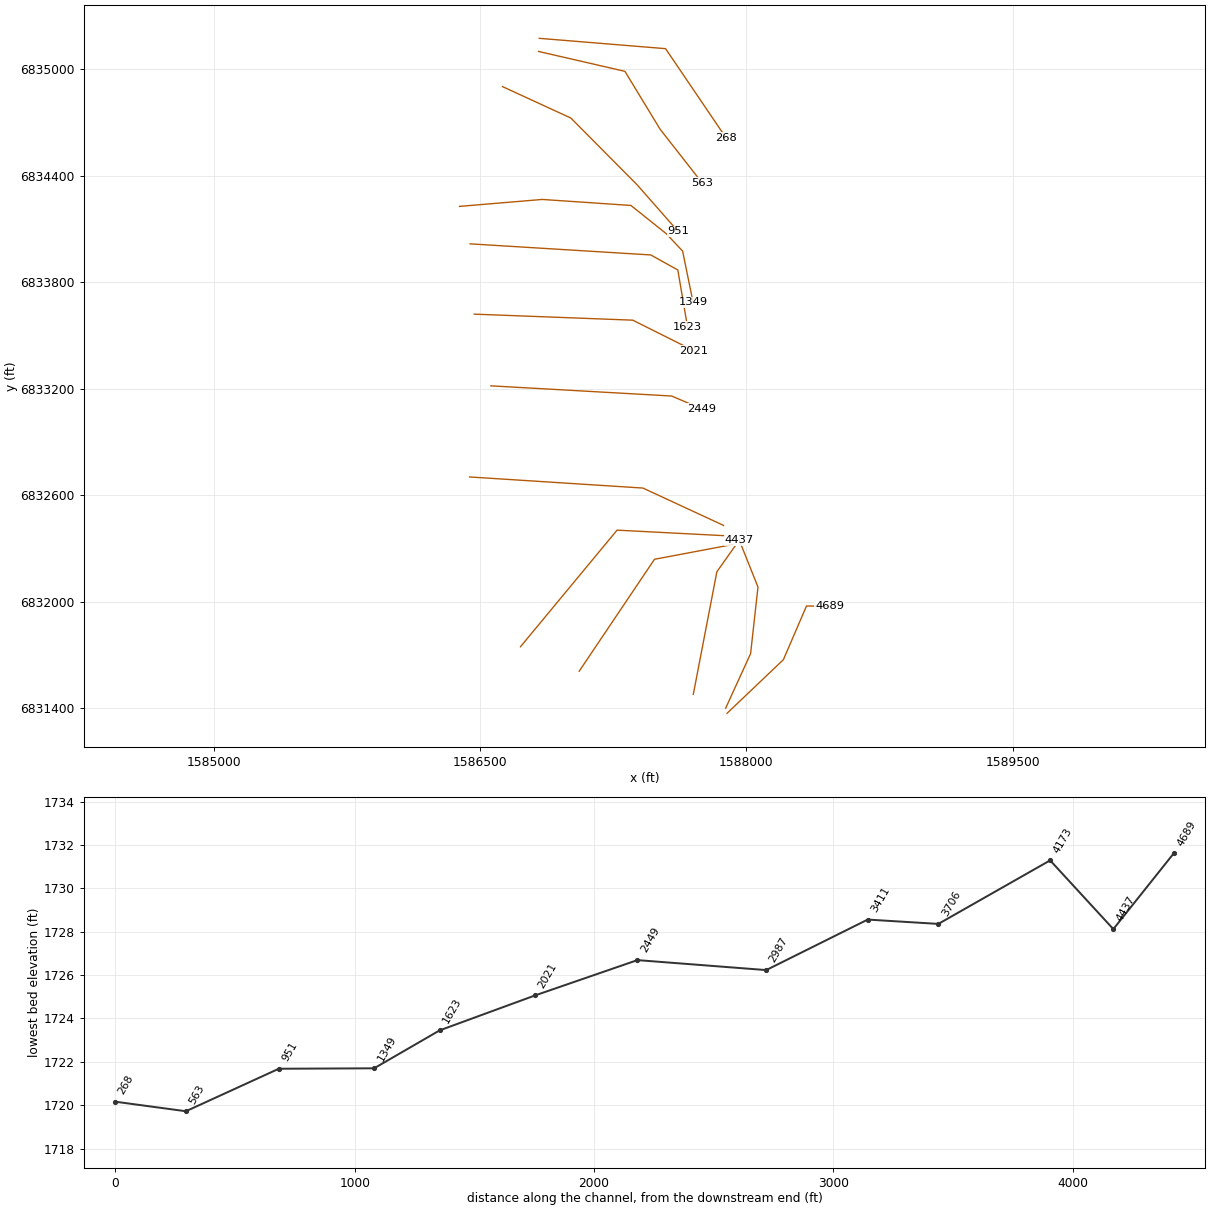
HEC-RAS study Buttonwillow Creek.prj: Buttonwillow Creek Base Level Engineering

--- Buttonwillow Creek.g01 (geometry) --- (continued)

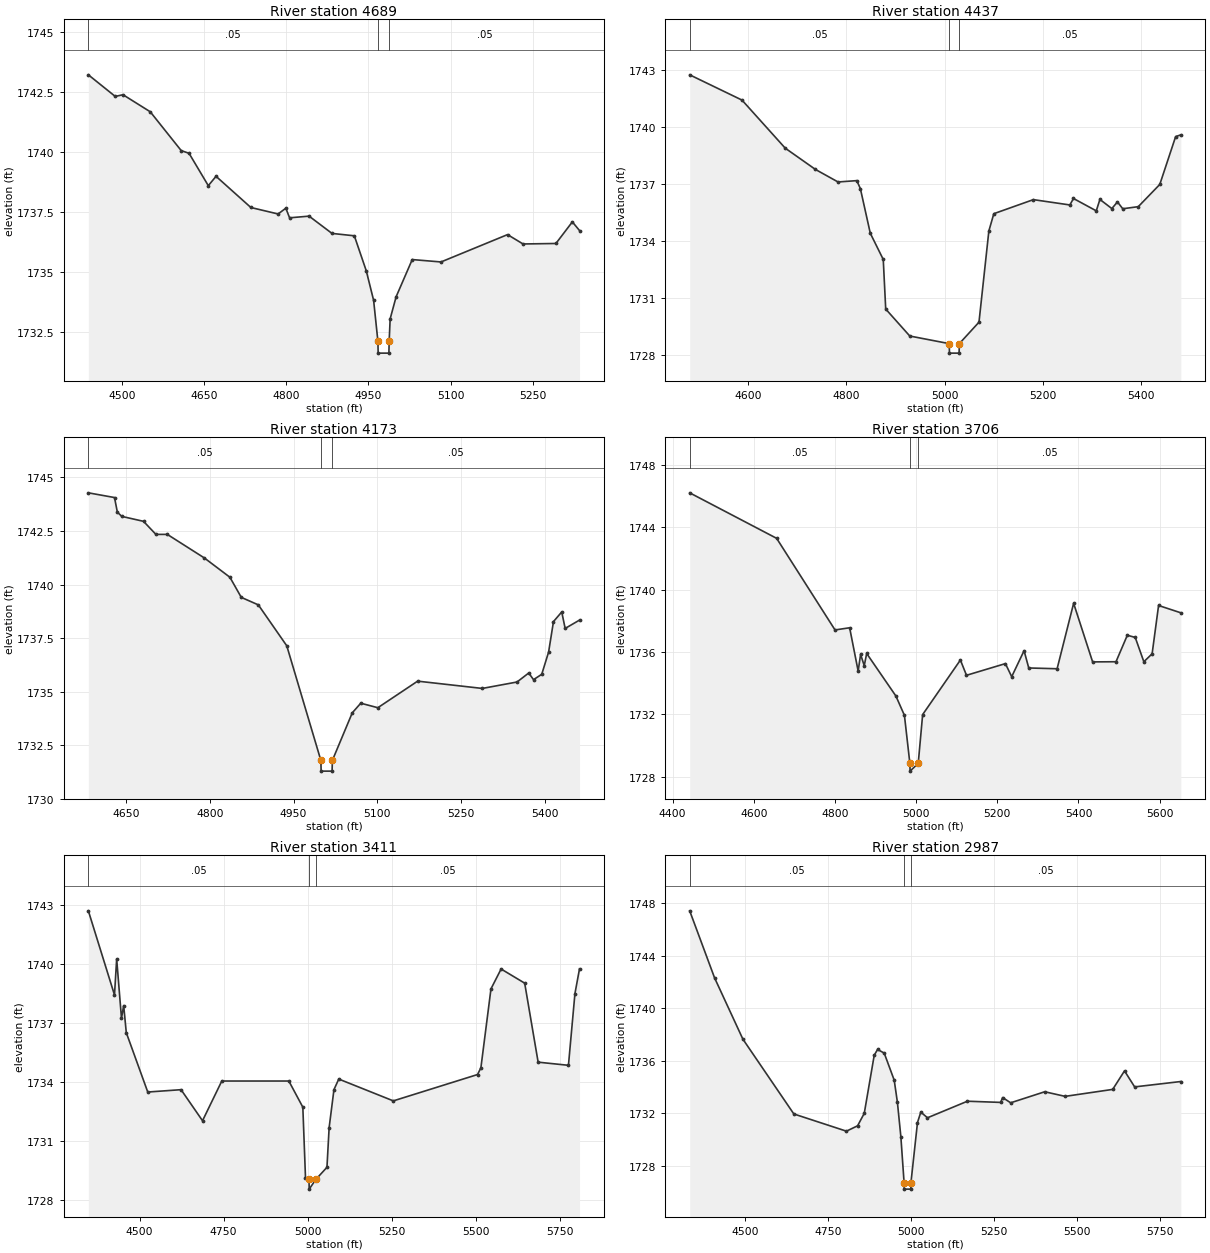
Type RM Length L Ch R = 1 ,4689    ,252,252,252
BEGIN DESCRIPTION:
Mapping XS 98d1637c
END DESCRIPTION:
XS GIS Cut Line= 4
      1587890.86      6831372.54      1588208.56       6831674.6
      1588338.76      6831976.69      1588468.13      6831975.33
#Sta/Elev= 30
  4438.8 1743.21  4487.9 1742.31  4502.1 1742.38  4551.8 1741.67  4608.4 1740.05
  4622.6 1739.94  4657.8 1738.59  4671.9 1738.98  4735.5 1737.68  4785.2 1737.41
  4799.3 1737.65  4806.2 1737.25  4841.8 1737.32  4883.6  1736.6  4924.4  1736.5
  4946.2 1735.04  4959.6 1733.81  4967.4 1732.11  4967.9 1731.61  4987.5 1731.61
    4988 1732.11  4989.8 1733.04  5000.7 1733.96  5030.1 1735.51  5082.6 1735.41
  5204.1 1736.55  5232.4 1736.16  5292.4 1736.18  5322.4 1737.08  5335.5 1736.72
#Mann= 3 ,-1 , 0
  4438.8     .05       0  4967.4     .03       0    4988     .05       0
Bank Sta=4967.4,4988
XS Rating Curve= 0 ,0
Exp/Cntr=0.3,0.1

Type RM Length L Ch R = 1 ,4437    ,264,264,264
BEGIN DESCRIPTION:
Mapping XS b2cf1c3c
END DESCRIPTION:
XS GIS Cut Line= 4
      1587883.04      6831401.17      1588023.66      6831708.46
      1588065.33      6832083.46      1587959.51      6832347.83
#Sta/Elev= 30
  4481.2 1742.77  4587.7 1741.44  4675.7 1738.91  4737.2 1737.79  4783.2 1737.13
  4821.4  1737.2  4828.7 1736.78  4848.9 1734.43  4875.3 1733.05  4880.3 1730.44
  4929.3 1729.02  5009.6 1728.62  5010.1 1728.12  5029.7 1728.12  5030.2 1728.62
  5070.2 1729.75  5090.3 1734.55  5100.4 1735.46  5180.9  1736.2  5255.2 1735.92
  5262.6 1736.26    5309 1735.61  5316.4 1736.21  5340.7 1735.73  5352.1 1736.08
  5362.9 1735.72  5394.5 1735.83  5438.3    1737  5470.6 1739.52  5481.2 1739.61
#Mann= 3 ,-1 , 0
  4481.2     .05       0  5009.6     .03       0  5030.2     .05       0
Bank Sta=5009.6,5030.2
XS Rating Curve= 0 ,0
Exp/Cntr=0.3,0.1

Type RM Length L Ch R = 1 ,4173    ,467,467,467
BEGIN DESCRIPTION:
Mapping XS f23fca78
END DESCRIPTION:
XS GIS Cut Line= 3
      1587700.74      6831479.28      1587833.56      6832169.39
      1587935.41      6832313.19
#Sta/Elev= 30
  4582.8 1744.28  4629.6 1744.06  4634.7 1743.38  4642.6 1743.18  4681.5 1742.95
  4703.7 1742.34  4724.1 1742.34  4790.4 1741.24  4836.1 1740.34  4856.5  1739.4
    4887 1739.05  4937.9 1737.14  4998.9 1731.79  4999.4 1731.29    5019 1731.29
  5019.5 1731.79  5055.1 1734.01  5070.3 1734.46  5100.9 1734.25  5172.1 1735.49
  5287.8 1735.15    5350 1735.45  5370.9 1735.87  5379.5 1735.56  5394.2 1735.81
  5406.5 1736.85  5415.2 1738.27    5430 1738.72  5436.1 1737.95  5461.8 1738.34
#Mann= 3 ,-1 , 0
  4582.8     .05       0  4998.9     .03       0  5019.5     .05       0
Bank Sta=4998.9,5019.5
XS Rating Curve= 0 ,0
Exp/Cntr=0.3,0.1

Type RM Length L Ch R = 1 ,3706    ,295,295,295
BEGIN DESCRIPTION:
Mapping XS 2b247f22
END DESCRIPTION:
XS GIS Cut Line= 3
      1587057.53      6831609.53      1587481.99      6832239.71
      1587924.62      6832323.03
#Sta/Elev= 30
  4442.1 1746.22  4656.3  1743.3  4800.2 1737.42  4836.2 1737.56  4857.2 1734.78
  4863.2 1735.85  4872.2 1735.13  4878.2 1735.91  4950.2 1733.18  4971.2 1731.94
  4984.6 1728.86  4985.1 1728.36  5005.2 1728.86  5016.1 1731.99  5109.1 1735.49
  5124.1 1734.51    5220 1735.26  5235.5 1734.42    5266 1736.09  5277.5 1734.98
  5347.4 1734.93  5388.1 1739.13  5434.9 1735.37  5492.5 1735.38  5520.4 1737.08
  5539.9 1736.94  5561.1 1735.38  5581.5 1735.89  5597.4 1738.99  5652.3 1738.52
#Mann= 3 ,-1 , 0
  4442.1     .05       0  4984.6     .03       0  5005.2     .05       0
Bank Sta=4984.6,5005.2
XS Rating Curve= 0 ,0
Exp/Cntr=0.3,0.1

Type RM Length L Ch R = 1 ,3411    ,424,424,424
BEGIN DESCRIPTION:
Mapping XS 72ee9909
END DESCRIPTION:
XS GIS Cut Line= 3
      1586726.81      6831747.55      1587271.06      6832403.77
      1587877.81      6832372.52
#Sta/Elev= 30
  4347.8 1742.72  4425.5 1738.44    4432 1740.27  4446.3 1737.25  4452.8  1737.9
  4460.6 1736.52  4524.4  1733.5  4623.4 1733.62  4687.2 1732.04  4744.5 1734.06
  4943.8 1734.06  4985.4 1732.73  4993.3 1729.15  5003.8 1729.06  5004.3 1728.56
  5024.4 1729.06  5057.1 1729.67  5063.6 1731.69  5077.9 1733.62  5092.2 1734.16
  5254.4 1733.05  5504.7 1734.39  5514.7 1734.73  5544.7 1738.75  5574.8 1739.76
  5644.9 1739.04  5684.9 1735.02    5775 1734.86  5794.3 1738.51  5807.9 1739.77
#Mann= 3 ,-1 , 0
  4347.8     .05       0  5003.8     .03       0  5024.4     .05       0
Bank Sta=5003.8,5024.4
XS Rating Curve= 0 ,0
Exp/Cntr=0.3,0.1

Type RM Length L Ch R = 1 ,2987    ,538,538,538
BEGIN DESCRIPTION:
Mapping XS 1ff559ce
END DESCRIPTION:
XS GIS Cut Line= 3
       1586440.3      6832703.25      1587416.89      6832640.75
      1587871.28      6832430.43
#Sta/Elev= 30
  4333.8 1747.41  4408.7 1742.31  4494.1 1737.64  4647.5 1731.95  4805.9 1730.64
  4839.5 1731.05  4859.6    1732  4889.6 1736.42  4899.7 1736.86  4919.7 1736.58
  4949.8 1734.52  4959.4 1732.84  4969.8 1730.22  4979.5 1726.73    4980 1726.23
  4999.7 1726.23  5000.2 1726.73  5019.9  1731.3  5029.9 1732.09    5050 1731.66
  5170.2 1732.92  5270.4 1732.83  5276.3  1733.2  5300.5  1732.8  5403.1 1733.64
  5464.6 1733.29  5607.8 1733.82  5643.4 1735.23  5673.9 1734.01  5813.1 1734.42
#Mann= 3 ,-1 , 0
  4333.8     .05       0  4979.5     .03       0  5000.2     .05       0
Bank Sta=4979.5,5000.2
XS Rating Curve= 0 ,0
Exp/Cntr=0.3,0.1

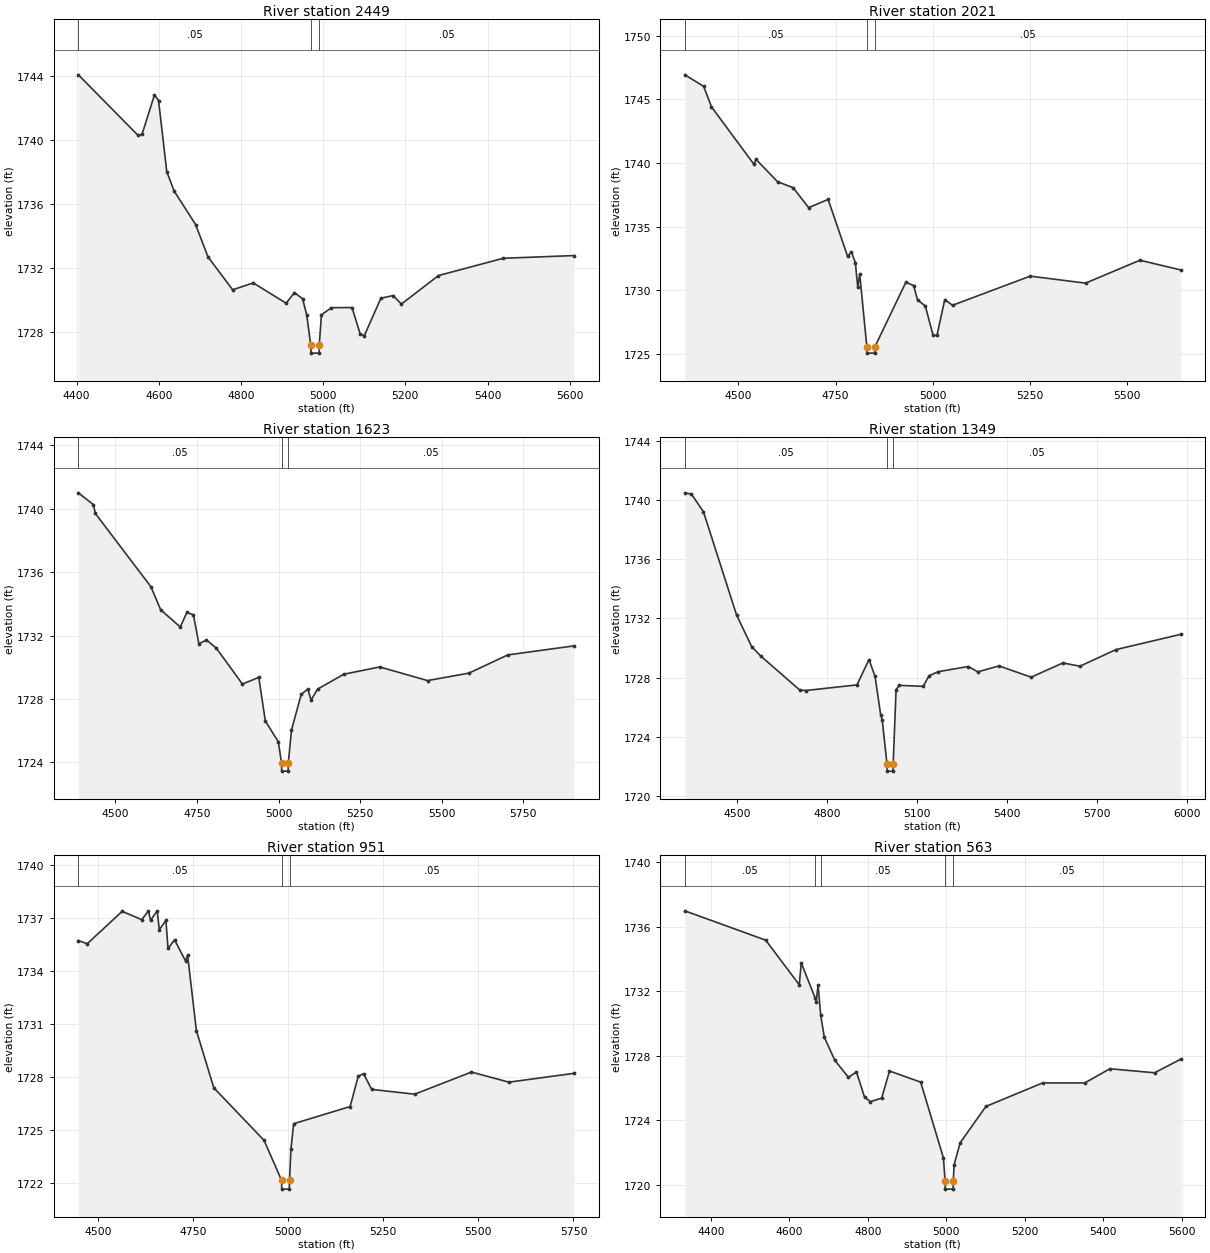
Type RM Length L Ch R = 1 ,2449    ,428,428,428
BEGIN DESCRIPTION:
Mapping XS 29a4bd3a
END DESCRIPTION:
XS GIS Cut Line= 3
      1586560.11      6833216.27      1587578.35      6833158.98
      1587750.08      6833086.12
#Sta/Elev= 30
  4404.4 1744.09  4549.5 1740.31  4559.5 1740.38  4589.6 1742.83  4599.6 1742.48
  4619.6 1738.03  4637.6 1736.82  4689.7 1734.73  4719.8 1732.71  4779.9 1730.65
    4830 1731.08  4910.1 1729.81  4930.1 1730.48  4950.2 1730.08  4960.2 1729.06
  4969.9 1727.19  4970.4 1726.69  4990.1 1726.69  4990.6 1727.19  4995.9 1729.09
  5020.3 1729.53  5070.3 1729.54  5090.4 1727.87  5100.4 1727.79  5140.5 1730.12
  5170.1 1730.29  5190.5 1729.76  5280.7 1731.54  5438.2 1732.62  5610.8 1732.79
#Mann= 3 ,-1 , 0
  4404.4     .05       0  4969.9     .03       0  4990.6     .05       0
Bank Sta=4969.9,4990.6
XS Rating Curve= 0 ,0
Exp/Cntr=0.3,0.1

Type RM Length L Ch R = 1 ,2021    ,398,398,398
BEGIN DESCRIPTION:
Mapping XS a9404465
END DESCRIPTION:
XS GIS Cut Line= 3
      1586466.32      6833619.92       1587359.6      6833586.06
       1587701.7      6833415.01
#Sta/Elev= 30
    4362 1746.93  4410.7 1746.02  4430.7 1744.41  4540.2 1739.89  4545.2 1740.29
  4600.8 1738.53  4640.9 1738.06  4680.9 1736.49  4730.9 1737.14    4781 1732.68
    4791    1733    4801 1732.17  4807.3 1730.24  4812.3 1731.28  4830.6 1725.56
  4831.1 1725.06  4850.9 1725.06  4851.4 1725.56  4931.1 1730.63  4951.1 1730.37
  4961.1 1729.24  4981.1 1728.77  5001.1 1726.46  5011.1 1726.45  5031.2 1729.26
  5051.2 1728.82  5251.1 1731.11  5393.7 1730.56  5533.5 1732.36  5638.4  1731.6
#Mann= 3 ,-1 , 0
    4362     .05       0  4830.6     .03       0  4851.4     .05       0
Bank Sta=4830.6,4851.4
XS Rating Curve= 0 ,0
Exp/Cntr=0.3,0.1

Type RM Length L Ch R = 1 ,1623    ,274,274,274
BEGIN DESCRIPTION:
Mapping XS d3ca8d6d
END DESCRIPTION:
XS GIS Cut Line= 4
      1586442.97      6834015.75      1587461.16      6833953.25
      1587613.44      6833868.65      1587668.23       6833547.8
#Sta/Elev= 30
  4386.3    1741  4432.3 1740.26  4438.4  1739.7  4608.7 1735.08  4638.8 1733.62
  4698.9 1732.54    4719 1733.46    4739 1733.31  4755.8 1731.48  4779.1 1731.72
  4809.1 1731.21  4889.3 1728.94  4939.4 1729.36  4959.4 1726.62  4999.5 1725.29
  5009.1 1723.95  5009.6 1723.45  5029.4 1723.45  5029.9 1723.95  5039.6 1726.03
  5069.6  1728.3  5089.6 1728.62  5099.7 1727.93  5119.7 1728.62  5199.9 1729.56
  5310.1 1730.02  5456.6 1729.16  5583.5 1729.63    5703 1730.78  5906.1 1731.35
#Mann= 3 ,-1 , 0
  4386.3     .05       0  5009.1     .04       0  5029.9     .05       0
Bank Sta=5009.1,5029.9
XS Rating Curve= 0 ,0
Exp/Cntr=0.3,0.1

Type RM Length L Ch R = 1 ,1349    ,398,398,398
BEGIN DESCRIPTION:
Mapping XS d5ced919
END DESCRIPTION:
XS GIS Cut Line= 6
      1586383.04      6834226.69      1586849.18      6834265.75
      1587349.18      6834231.89        1587548.      6834073.31
      1587640.45       6833974.9      1587699.47      6833686.75
#Sta/Elev= 30
  4325.1 1740.48  4347.1  1740.4  4387.3  1739.2  4497.7 1732.23  4547.8 1730.11
  4577.9 1729.47  4708.4 1727.17  4728.5 1727.14  4898.9 1727.52    4939 1729.23
  4959.1 1728.09  4977.8 1725.52  4982.9 1725.18  4998.8  1722.2  4999.3  1721.7
  5019.1  1721.7  5019.6  1722.2  5029.2 1727.19  5039.3 1727.49  5119.4 1727.42
  5139.5 1728.14  5169.6 1728.41  5269.8 1728.76  5301.5  1728.4  5372.1  1728.8
  5479.4 1728.04  5585.2    1729  5641.9 1728.78  5761.9  1729.9  5977.5 1730.93
#Mann= 3 ,-1 , 0
  4325.1     .05       0  4998.8     .04       0  5019.6     .05       0
Bank Sta=4998.8,5019.6
XS Rating Curve= 0 ,0
Exp/Cntr=0.3,0.1

Type RM Length L Ch R = 1 ,951     ,388,388,388
BEGIN DESCRIPTION:
Mapping XS 851d59f3
END DESCRIPTION:
XS GIS Cut Line= 4
      1586625.23      6834901.16      1587010.64      6834724.08
      1587385.64      6834346.48       1587614.8      6834086.07
#Sta/Elev= 30
  4448.6 1735.74    4472 1735.56  4563.9 1737.39  4615.4 1736.92  4632.9 1737.42
  4638.4 1736.88  4655.9 1737.42  4661.4 1736.35  4678.8 1736.88  4684.3 1735.29
  4701.5 1735.78  4730.3 1734.59  4735.8 1734.91  4758.8 1730.65  4804.7 1727.41
  4936.7 1724.44  4982.8 1722.18  4983.3 1721.68  5003.2 1721.68  5003.7 1722.18
  5007.4 1723.95  5014.5 1725.38    5163 1726.35  5184.2 1728.06  5198.3 1728.21
  5219.6 1727.32  5332.7 1727.05  5481.7  1728.3  5580.4 1727.73  5751.8 1728.23
#Mann= 3 ,-1 , 0
  4448.6     .05       0  4982.8     .04       0  5003.7     .05       0
Bank Sta=4982.8,5003.7
XS Rating Curve= 0 ,0
Exp/Cntr=0.3,0.1

Type RM Length L Ch R = 1 ,563     ,295,295,295
BEGIN DESCRIPTION:
Mapping XS e51364ab
END DESCRIPTION:
XS GIS Cut Line= 4
      1586828.37      6835099.08      1587315.33       6834987.1
      1587513.24      6834661.58      1587750.11      6834359.64
#Sta/Elev= 30
  4333.2 1736.99  4539.5 1735.17  4625.1  1732.4  4630.2 1733.76  4665.4 1731.59
    4668 1731.34  4673.1 1732.36  4679.8 1730.51  4688.9 1729.15  4715.9 1727.71
  4750.4 1726.66    4771 1726.99  4791.5 1725.43  4806.7 1725.15  4835.3 1725.37
  4855.2 1727.05  4934.7 1726.36  4992.8 1721.65  4996.9 1720.22  4997.4 1719.72
  5017.4 1719.72  5017.9 1720.22    5020 1721.24  5035.5  1722.6    5101 1724.85
  5245.6 1726.31  5353.1 1726.31  5417.3 1727.19  5531.2 1726.94  5597.6 1727.78
#Mann= 5 ,-1 , 0
  4333.2     .05       0  4665.4    .075       0  4679.8     .05       0
  4996.9     .03       0  5017.9     .05       0
Bank Sta=4996.9,5017.9
XS Rating Curve= 0 ,0
Exp/Cntr=0.3,0.1

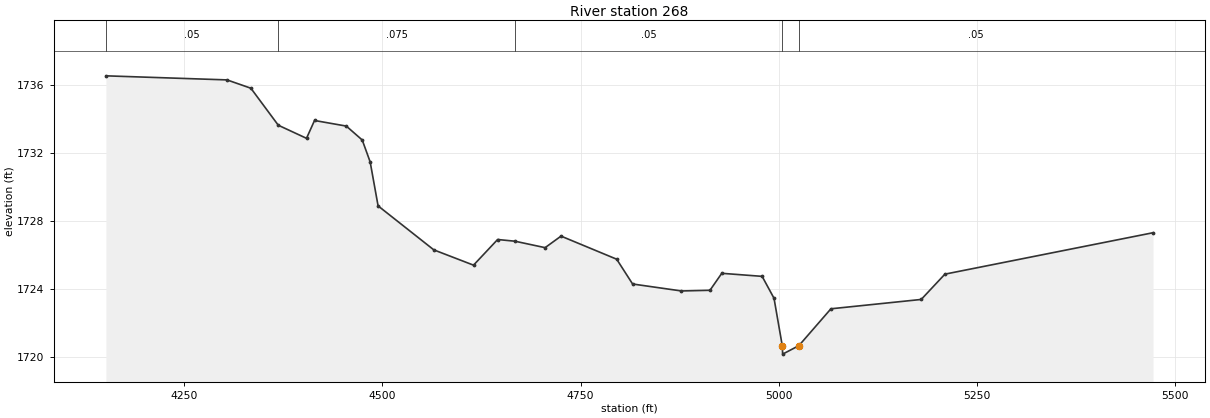
Type RM Length L Ch R = 1 ,268     ,0,0,0
BEGIN DESCRIPTION:
Buttonwillow Creek 10867.471
END DESCRIPTION:
XS GIS Cut Line= 3
       1586832.7      6835172.87      1587544.49      6835114.71
      1587885.35      6834612.53
#Sta/Elev= 30
  4151.2 1736.55    4304 1736.31  4334.1 1735.82  4368.7 1733.64  4404.3 1732.87
  4414.4 1733.92  4454.5 1733.59  4474.6 1732.77  4484.6 1731.48  4494.6 1728.89
  4564.9  1726.3    4615  1725.4  4645.4 1726.91  4667.3 1726.81  4705.3 1726.43
  4725.4 1727.11  4795.6 1725.75  4815.7 1724.29  4877.3 1723.88  4913.3 1723.92
  4928.2 1724.92  4979.1 1724.74  4994.1 1723.45  5004.5 1720.66    5005 1720.16
  5025.5 1720.66  5065.9 1722.83  5179.8 1723.38  5209.7 1724.87  5472.3 1727.31
#Mann= 5 ,-1 , 0
  4151.2     .05       0  4368.7    .075       0  4667.3     .05       0
  5004.5     .03       0  5025.5     .05       0
Bank Sta=5004.5,5025.5
XS Rating Curve= 0 ,0
Exp/Cntr=0.3,0.1

Chan Stop Cuts=-1
Use User Specified Reach Order=0
Composite Channel Slope=5