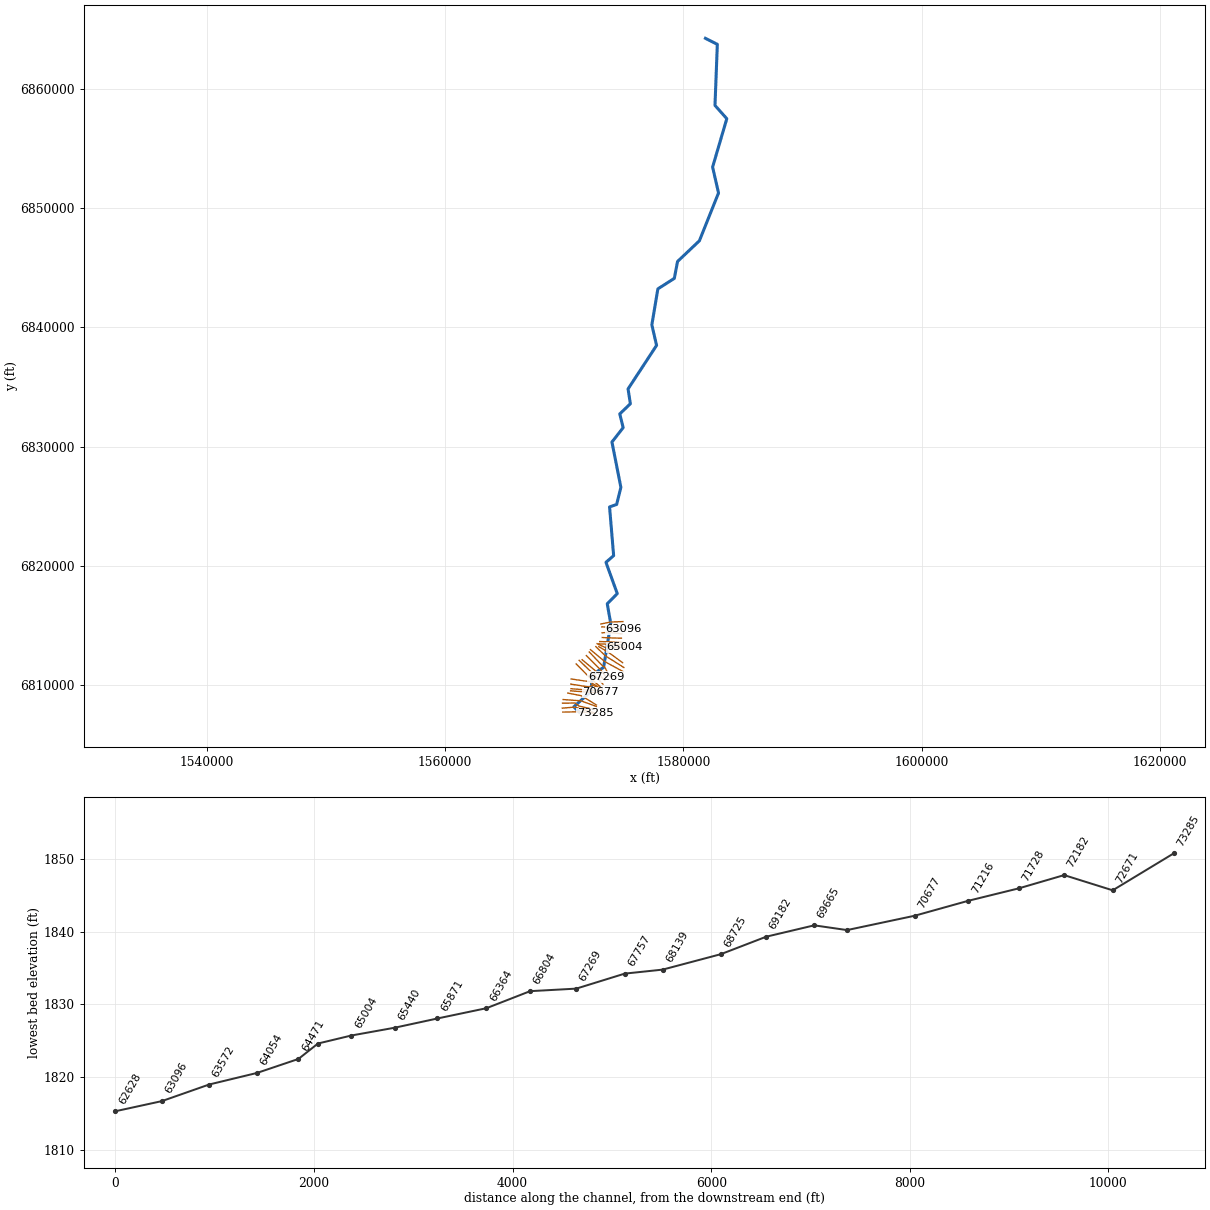
--- Cat Claw Creek.prj (project) ---

Proj Title=Cat Claw Creek Base Level Engineering
Current Plan=p01
Default Exp/Contr=0.3,0.1
English Units
Geom File=g01
Flow File=f01
Plan File=p01
Y Axis Title=Elevation
X Axis Title(PF)=Main Channel Distance
X Axis Title(XS)=Station
BEGIN DESCRIPTION:
Cat Claw Creek
END DESCRIPTION:
DSS Export Rating Curves= 0
DSS Export Rating Curve Sorted= 0
DSS Export Volume Flow Curves= 0
DXF OffsetX= 0
DXF OffsetY= 0
DXF ScaleX= 1
DXF ScaleY= 10

--- Cat Claw Creek.p01 (plan) ---

Plan Title=Multiple Run
Program Version=4.10
Short Identifier=Multiple
Geom File=g01
Flow File=f01
Subcritical Flow
K Sum by GR= 0
Std Step Tol= 0.01
Critical Tol= 0.01
Num of Std Step Trials= 20
Max Error Tol= 0.3
Flow Tol Ratio= 0.001
Split Flow NTrial= 30
Split Flow Tol= 0.02
Split Flow Ratio= 0.02
Log Output Level= 0
Friction Slope Method= 1
Unsteady Friction Slope Method= 2
Unsteady Bridges Friction Slope Method= 1
Parabolic Critical Depth
Global Vel Dist= 1 , 1 , 1
Global Log Level= 0
CheckData=True
Encroach Param=-1 ,0,0, 0
BEGIN DESCRIPTION:
Multiple Run
END DESCRIPTION:
Computation Interval=1HOUR
Output Interval=1HOUR
Run HTab= 0
Run UNet= 0
Run PostProcess= 0
Run WQNet= 0
UNET Theta= 1
UNET Theta Warmup= 1
UNET ZTol= 0.02
UNET ZSATol= 0.05
UNET MxIter= 20
UNET MaxInSteps= 0
UNET DtIC= 0
UNET DtMin= 0
UNET MaxCRTS= 20
UNET WFStab= 2
UNET SFStab= 1
UNET WFX= 1
UNET SFX= 1
UNET DSS MLevel= 4
UNET DZMax Abort= 100
UNET Convert EG Bridges= 0
UNET Use Existing IB Tables=-1
UNET Froude Reduction=False
UNET Froude Limit= 1
UNET Froude Power= 10
UNET Time Slicing=0,0, 5
UNET Junction Losses=0
Instantaneous Interval=1HOUR
Write IC File= 0
Write IC File at Sim End=0
Echo Input=False
Echo Parameters=False
Echo Output=False
Write Detailed= 0
WQ AD Non Conservative
WQ ULTIMATE=-1
WQ Max Comp Step=1HOUR
WQ Output Interval=15MIN
WQ Output Selected Increments= 0
WQ Output face flow=0
WQ Output face velocity=0
WQ Output face area=0
WQ Output face dispersion=0
WQ Output cell volume=0
WQ Output cell surface area=0
WQ Output cell continuity=0
WQ Output cumulative cell continuity=0
WQ Output face conc=0
WQ Output face dconc_dx=0
WQ Output face courant=0
WQ Output face peclet=0
WQ Output face adv mass=0
WQ Output face disp mass=0
WQ Output cell mass=0
WQ Output cell source sink temp=0
WQ Output cell source sink nsm=0
WQ Output MaxMinRange=-1
WQ Daily Max Min Mean=-1
WQ Daily Range=0
WQ Daily Time=0
WQ Create Restart=0
WQ Fixed Restart=0
WQ System Summary=0
WQ Use Fixed Temperature=0
Sorting and Armoring Iterations= 10
XS Update Threshold= 0.02
Hydraulics Update Threshold= 0.02
Energy Slope Method= 1
Volume Change Method= 0
XS Weighting Method= 0
Number of US Weighted Cross Sections= 1
Number of DS Weighted Cross Sections= 1
Upstream XS Weight=0.25
Main XS Weight=0.5
Downstream XS Weight=0.25
Number of DS XS's Weighted with US Boundary= 1
Upstream Boundary Weight= 1
Weight of XSs Associated with US Boundary= 0
Number of US XS's Weighted with DS Boundary= 1
Downstream Boundary Weight= 0.5
Weight of XSs Associated with DS Boundary= 0.5
Sediment Output Level= 4
Mass or Volume Output= 0
Output Increment Type= 1
Profile and TS Output Increment= 10
XS Output Flag= 0
XS Output Increment= 10
Disregard all LS=0
Disregard all Conn=0
Disregard all Breaches=0
Disregard all Pumps=0

--- Cat Claw Creek.f01 (steady flow) ---

Flow Title=Multiple
Number of Profiles=7
Profile Names=10-year,25-year,50-year,1pct_min,100-year,1pct_plu,500-year
River Rch & RM= Cat Claw Creek,Reach-1,73285
     198     269     327     197     394     786     581
River Rch & RM= Cat Claw Creek,Reach-1,72671
     294     408     501     306     610    1217     918
River Rch & RM= Cat Claw Creek,Reach-1,65004
     375     525     649     398     795    1586    1210
River Rch & RM= Cat Claw Creek,Reach-1,56336
     562     799     998     619    1235    2463    1916
River Rch & RM= Cat Claw Creek,Reach-1,46496
     605     861    1078     668    1334    2661    2072
River Rch & RM= Cat Claw Creek,Reach-1,40859
     650     928    1163     722    1441    2876    2246
River Rch & RM= Cat Claw Creek,Reach-1,38505
     701    1001    1256     781    1557    3107    2430
River Rch & RM= Cat Claw Creek,Reach-1,29135
     790    1135    1429     891    1778    3547    2793
River Rch & RM= Cat Claw Creek,Reach-1,24780
     892    1287    1624    1015    2026    4042    3196
River Rch & RM= Cat Claw Creek,Reach-1,18578
     932    1346    1700    1063    2122    4233    3352
River Rch & RM= Cat Claw Creek,Reach-1,14103
     977    1412    1785    1117    2229    4448    3525
River Rch & RM= Cat Claw Creek,Reach-1,8751
    1009    1460    1846    1156    2306    4601    3650
Boundary for River Rch & Prof#=Cat Claw Creek,Reach-1,1
Up Type=0
Dn Type=3
Dn Slope=0.004
Boundary for River Rch & Prof#=Cat Claw Creek,Reach-1,2
Up Type=0
Dn Type=3
Dn Slope=0.004
Boundary for River Rch & Prof#=Cat Claw Creek,Reach-1,3
Up Type=0
Dn Type=3
Dn Slope=0.004
Boundary for River Rch & Prof#=Cat Claw Creek,Reach-1,4
Up Type=0
Dn Type=3
Dn Slope=0.004
Boundary for River Rch & Prof#=Cat Claw Creek,Reach-1,5
Up Type=0
Dn Type=3
Dn Slope=0.004
Boundary for River Rch & Prof#=Cat Claw Creek,Reach-1,6
Up Type=0
Dn Type=3
Dn Slope=0.004
Boundary for River Rch & Prof#=Cat Claw Creek,Reach-1,7
Up Type=0
Dn Type=3
Dn Slope=0.004

--- Cat Claw Creek.g01 (geometry) ---

Geom Title=Existing Conditions

River Reach=Cat Claw Creek,Reach-1
Reach XY= 30
      1571255.00      6807688.00      1570807.99      6808136.59
      1572247.20      6809431.17      1572360.86      6810840.86
      1573302.95      6811443.84      1573905.39      6815119.66
      1573612.23      6816787.71      1574452.83      6817643.44
      1573504.29      6820268.24      1574147.21      6820834.57
      1573805.24      6824923.90      1574399.66      6825135.26
      1574755.71      6826569.73      1574006.02      6830378.52
      1574947.17      6831584.60      1574662.56      6832738.00
      1575552.65      6833593.52      1575358.61      6834836.50
      1577752.94      6838493.86      1577354.89      6840222.23
      1577860.71      6843240.35      1579241.64      6844124.66
      1579512.85      6845544.19      1581347.14      6847281.83
      1582953.78      6851298.50      1582455.52      6853472.78
      1583647.50      6857538.00      1582655.08      6858653.39
      1582852.65      6863782.48      1581855.00      6864288.00

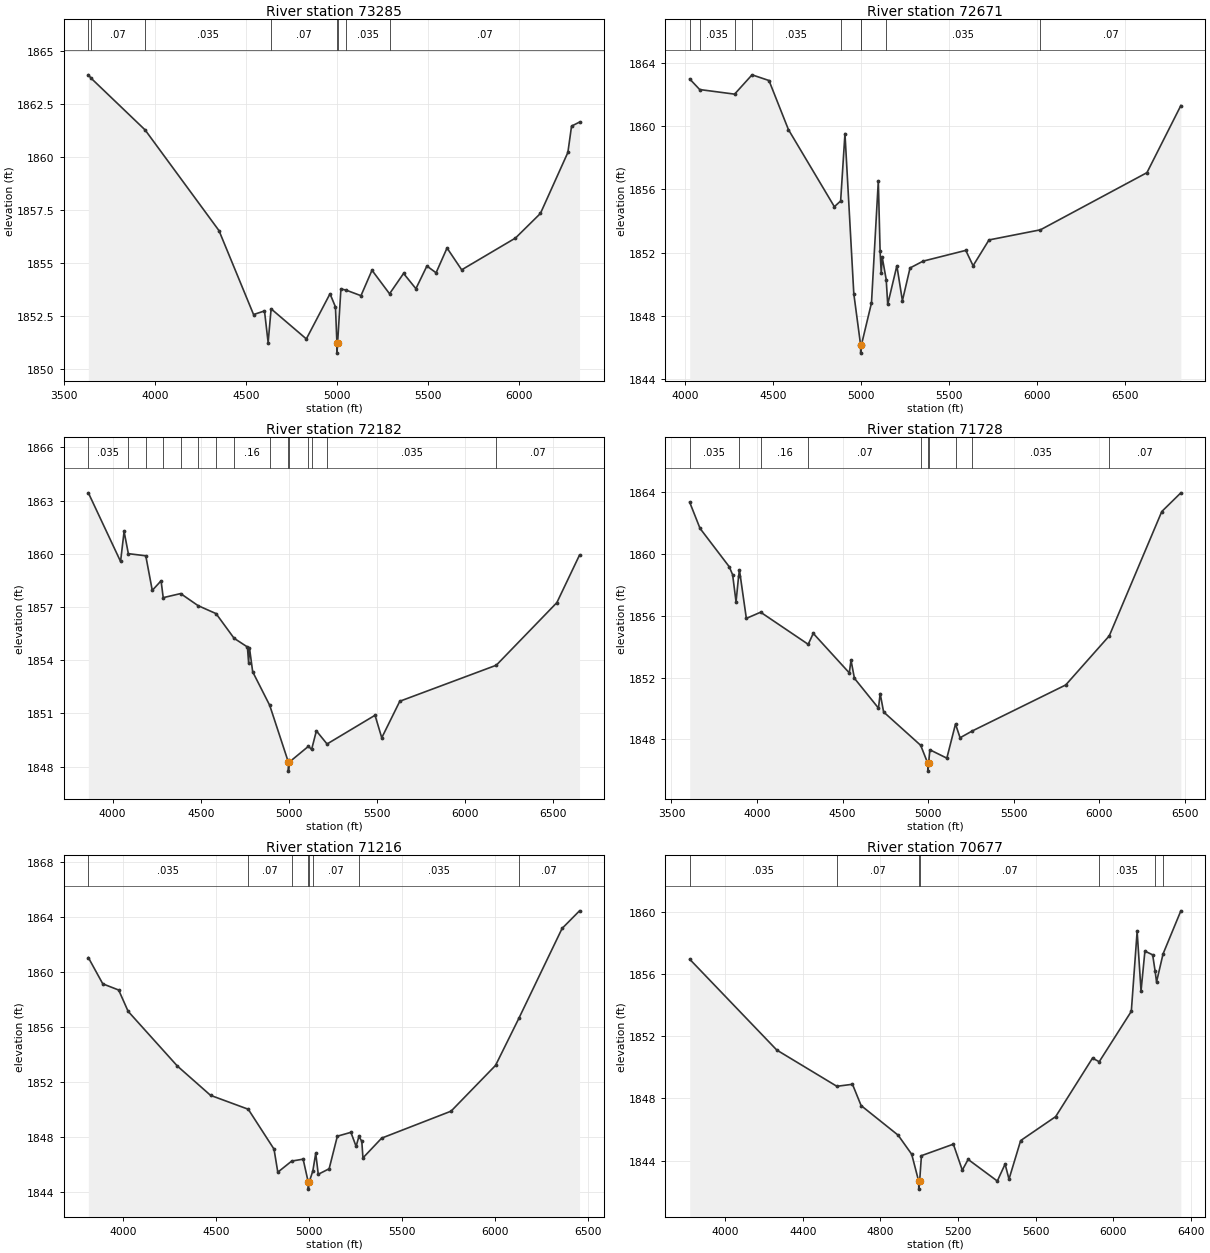
Type RM Length L Ch R = 1,73285,614,614,614
BEGIN DESCRIPTION:
Cat Claw Creek 90.0
END DESCRIPTION:
XS GIS Cut Line= 3
      1569887.10      6807689.32      1571350.19      6807723.32
      1572578.51      6807582.89
#Sta/Elev= 30
  3631.8 1863.86  3646.9 1863.70  3943.8 1861.26  4349.9 1856.51  4539.9 1852.55
  4600.0 1852.72  4620.0 1851.23  4636.4 1852.82  4830.0 1851.40  4960.1 1853.53
  4990.1 1852.91  4998.0 1851.23  4998.3 1850.73  5002.0 1851.23  5020.1 1853.76
  5049.4 1853.70  5130.3 1853.44  5190.9 1854.64  5287.4 1853.53  5364.5 1854.49
  5432.3 1853.77  5492.7 1854.84  5543.2 1854.52  5603.4 1855.69  5683.9 1854.66
  5979.6 1856.16  6116.7 1857.32  6267.7 1860.20  6287.8 1861.44  6331.6 1861.63
#Mann=8,-1,0
  3631.8   0.035       0  3646.9    0.07       0  3943.8   0.035       0
  4636.4    0.07       0  4998.0    0.07       0  5002.0    0.07       0
  5049.4   0.035       0  5287.4    0.07       0
Bank Sta=4998,5002
Exp/Cntr=0.3,0.1

Type RM Length L Ch R = 1,72671,489,489,489
BEGIN DESCRIPTION:
Cat Claw Creek 89.0
END DESCRIPTION:
XS GIS Cut Line= 4
      1569836.15      6808023.25      1570917.66      6808113.86
      1571353.15      6807965.69      1572550.32      6807626.51
#Sta/Elev= 30
  4027.1 1862.98  4083.9 1862.31  4282.1 1862.02  4381.2 1863.24  4477.5 1862.88
  4587.9 1859.78  4848.8 1854.91  4884.4 1855.27  4909.0 1859.53  4959.2 1849.41
  4998.0 1846.16  4998.2 1845.66  5002.1 1846.16  5059.6 1848.83  5098.4 1856.53
  5108.6 1852.08  5115.0 1850.70  5120.3 1851.73  5143.2 1850.31  5151.8 1848.74
  5203.8 1851.18  5235.2 1848.97  5278.6 1851.04  5352.5 1851.47  5595.1 1852.15
  5636.7 1851.18  5727.0 1852.81  6019.3 1853.45  6624.1 1857.06  6816.7 1861.30
#Mann=9,-1,0
  4027.1    0.07       0  4083.9   0.035       0  4282.1    0.07       0
  4381.2   0.035       0  4884.4    0.07       0  4998.0    0.07       0
  5002.1    0.07       0  5143.2   0.035       0  6019.3    0.07       0
Bank Sta=4998,5002.1
Exp/Cntr=0.3,0.1

Type RM Length L Ch R = 1,72182,454,454,454
BEGIN DESCRIPTION:
Cat Claw Creek 88.0
END DESCRIPTION:
XS GIS Cut Line= 4
      1569852.18      6808434.27      1570907.15      6808455.95
      1571256.70      6808191.95      1572520.51      6807908.25
#Sta/Elev= 30
  3862.2 1863.44  4045.1 1859.57  4065.1 1861.26  4089.3 1860.01  4188.2 1859.89
  4225.1 1857.94  4275.1 1858.48  4287.2 1857.53  4386.1 1857.76  4485.1 1857.08
  4587.3 1856.63  4689.6 1855.24  4765.2 1854.75  4772.0 1853.87  4777.0 1854.69
  4795.2 1853.35  4891.8 1851.46  4998.0 1848.25  4998.2 1847.75  5002.1 1848.25
  5111.8 1849.15  5129.7 1848.97  5156.8 1850.02  5217.4 1849.28  5489.8 1850.90
  5527.9 1849.63  5630.4 1851.69  6178.1 1853.72  6522.1 1857.25  6650.7 1859.93
#Mann=15,-1,0
  3862.2   0.035       0  4089.3    0.07       0  4188.2   0.035       0
  4287.2    0.07       0  4386.1   0.035       0  4485.1    0.16       0
  4587.3    0.07       0  4689.6    0.16       0  4891.8    0.07       0
  4998.0    0.07       0  5002.1    0.07       0  5111.8   0.035       0
  5129.7    0.07       0  5217.4   0.035       0  6178.1    0.07       0
Bank Sta=4998,5002.1
Exp/Cntr=0.3,0.1

Type RM Length L Ch R = 1,71728,512,512,512
BEGIN DESCRIPTION:
Cat Claw Creek 87.0
END DESCRIPTION:
XS GIS Cut Line= 3
      1569914.87      6808745.15      1571394.49      6808640.44
      1572696.94      6808165.69
#Sta/Elev= 30
  3606.7 1863.35  3667.0 1861.66  3837.4 1859.18  3857.5 1858.66  3877.5 1856.90
  3892.7 1858.58  3897.6 1858.95  3937.7 1855.83  4021.2 1856.23  4299.2 1854.15
  4328.6 1854.86  4539.2 1852.30  4549.2 1853.12  4569.2 1851.95  4709.6 1850.02
  4719.6 1850.96  4739.7 1849.77  4956.3 1847.61  4997.9 1846.44  4998.2 1845.94
  5002.1 1846.44  5010.3 1847.32  5109.1 1846.78  5159.7 1848.99  5186.4 1848.10
  5257.5 1848.54  5803.7 1851.52  6058.1 1854.70  6364.9 1862.75  6476.3 1863.96
#Mann=10,-1,0
  3606.7   0.035       0  3892.7    0.07       0  4021.2    0.16       0
  4299.2    0.07       0  4956.3    0.16       0  4997.9    0.07       0
  5002.1    0.16       0  5159.7    0.07       0  5257.5   0.035       0
  6058.1    0.07       0
Bank Sta=4997.9,5002.1
Exp/Cntr=0.3,0.1

Type RM Length L Ch R = 1,71216,539,539,539
BEGIN DESCRIPTION:
Cat Claw Creek 86.0
END DESCRIPTION:
XS GIS Cut Line= 3
      1570304.99      6809288.00      1571414.48      6809073.05
      1572705.03      6808287.98
#Sta/Elev= 30
  3815.3 1861.06  3892.9 1859.15  3978.3 1858.70  4029.2 1857.15  4294.0 1853.17
  4472.4 1851.04  4675.0 1850.03  4813.5 1847.13  4833.9 1845.45  4908.6 1846.26
  4970.0 1846.40  4997.7 1844.72  4998.1 1844.22  5002.3 1844.72  5022.4 1845.55
  5037.8 1846.83  5051.4 1845.30  5109.9 1845.70  5154.0 1848.07  5226.9 1848.35
  5254.8 1847.33  5269.9 1848.05  5285.5 1847.70  5291.6 1846.49  5392.4 1847.93
  5765.4 1849.89  6004.6 1853.22  6129.8 1856.64  6362.3 1863.18  6456.0 1864.46
#Mann=8,-1,0
  3815.3   0.035       0  4675.0    0.07       0  4908.6   0.035       0
  4997.7   0.035       0  5002.3   0.035       0  5022.4    0.07       0
  5269.9   0.035       0  6129.8    0.07       0
Bank Sta=4997.7,5002.3
Exp/Cntr=0.3,0.1

Type RM Length L Ch R = 1,70677,681,681,681
BEGIN DESCRIPTION:
Cat Claw Creek 85.2
END DESCRIPTION:
XS GIS Cut Line= 3
      1570533.83      6809477.75      1572329.07      6809338.90
      1573060.26      6809360.27
#Sta/Elev= 30
  3817.0 1856.95  4266.1 1851.11  4575.7 1848.78  4656.2 1848.91  4700.8 1847.54
  4891.4 1845.64  4961.6 1844.41  4997.7 1842.67  4998.0 1842.17  5002.4 1842.67
  5011.7 1844.32  5176.3 1845.06  5222.4 1843.39  5252.4 1844.08  5402.9 1842.69
  5443.0 1843.78  5463.1 1842.81  5523.2 1845.29  5703.6 1846.83  5893.6 1850.59
  5928.3 1850.36  6093.7 1853.60  6123.7 1858.74  6143.8 1854.91  6163.8 1857.47
  6203.8 1857.23  6216.3 1856.19  6223.8 1855.49  6257.3 1857.29  6349.1 1860.06
#Mann=7,-1,0
  3817.0   0.035       0  4575.7    0.07       0  4997.7    0.07       0
  5002.4    0.07       0  5928.3   0.035       0  6216.3    0.07       0
  6257.3   0.035       0
Bank Sta=4997.7,5002.4
Exp/Cntr=0.3,0.1

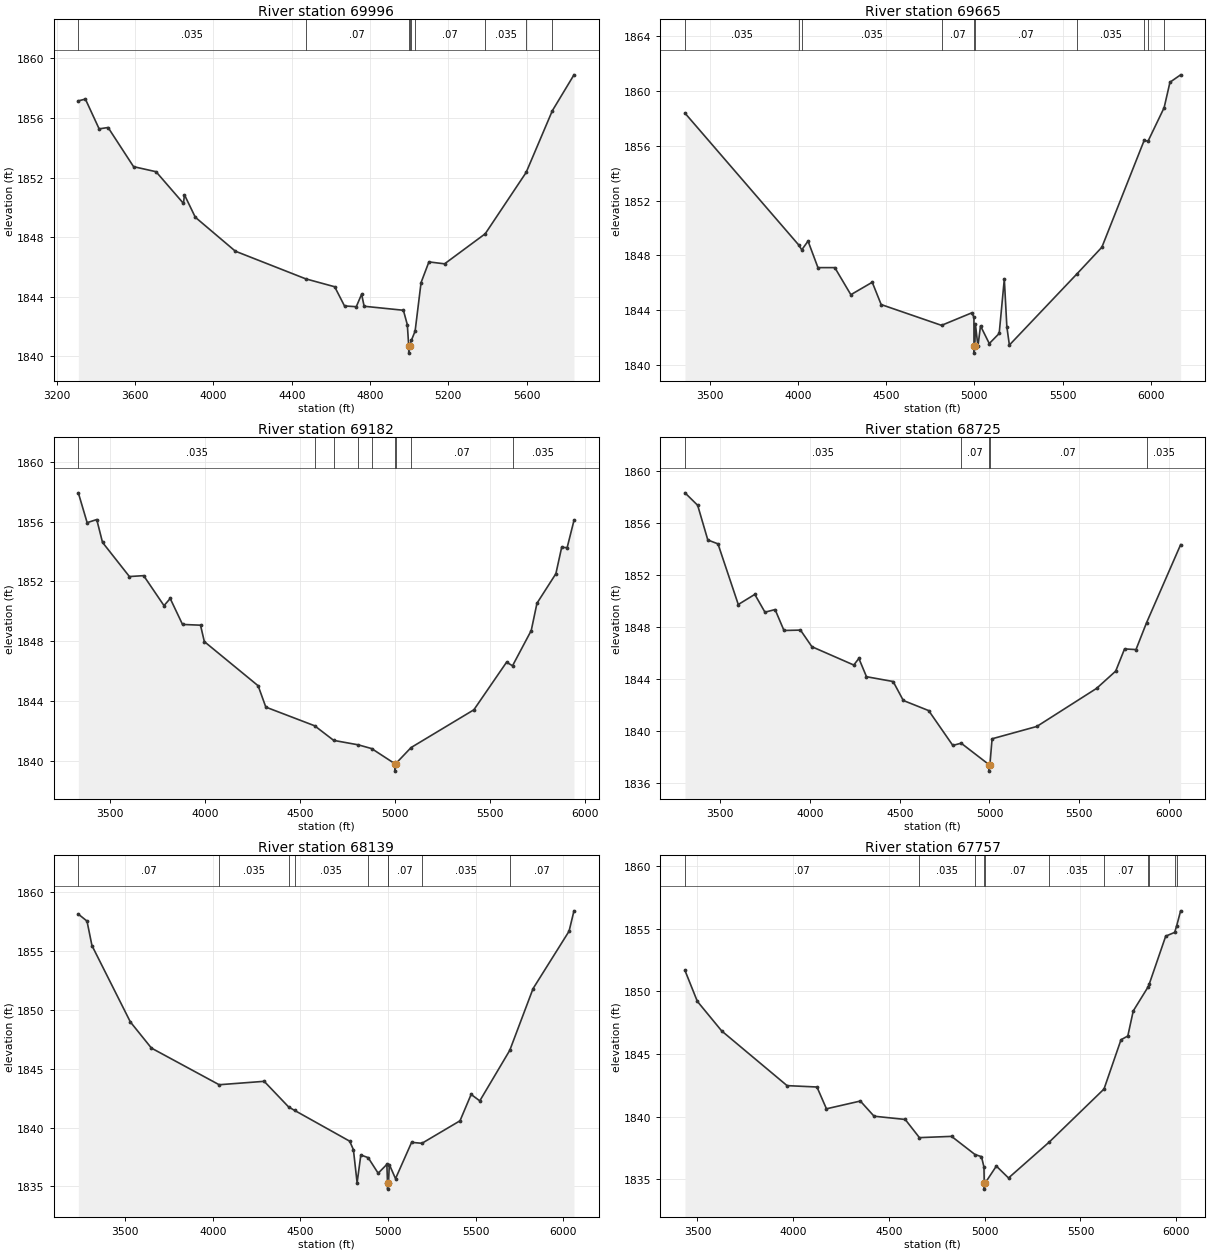
Type RM Length L Ch R = 1,69996,331,331,331
BEGIN DESCRIPTION:
Cat Claw Creek 85.0
END DESCRIPTION:
XS GIS Cut Line= 3
      1570569.05      6809654.79      1572364.30      6809515.94
      1573095.88      6809537.32
#Sta/Elev= 30
  3309.6 1857.15  3345.7 1857.27  3415.9 1855.27  3461.7 1855.36  3591.8 1852.73
  3706.7 1852.39  3846.8 1850.26  3851.8 1850.84  3907.3 1849.33  4111.9 1847.05
  4471.8 1845.19  4619.4 1844.66  4669.6 1843.37  4729.8 1843.32  4757.1 1844.16
  4769.9 1843.35  4970.5 1843.08  4990.6 1842.11  4997.6 1840.70  4998.0 1840.20
  5002.4 1840.70  5011.1 1841.05  5030.4 1841.68  5060.8 1844.94  5100.9 1846.33
  5180.9 1846.20  5388.6 1848.22  5597.6 1852.34  5731.6 1856.49  5842.1 1858.90
#Mann=9,-1,0
  3309.6   0.035       0  4471.8    0.07       0  4997.6    0.07       0
  5002.4    0.07       0  5011.1   0.035       0  5030.4    0.07       0
  5388.6   0.035       0  5597.6    0.07       0  5731.6   0.035       0
Bank Sta=4997.6,5002.4
Exp/Cntr=0.3,0.1

Type RM Length L Ch R = 1,69665,483,483,483
BEGIN DESCRIPTION:
Cat Claw Creek 84.0
END DESCRIPTION:
XS GIS Cut Line= 4
      1570554.97      6810038.00      1572125.19      6809795.90
      1572358.88      6809974.84      1573199.26      6809579.34
#Sta/Elev= 30
  3358.0 1858.39  4002.2 1848.77  4020.6 1848.40  4056.2 1849.04  4112.3 1847.10
  4208.0 1847.10  4299.0 1845.12  4420.4 1846.03  4471.0 1844.40  4813.4 1842.88
  4984.3 1843.79  4997.3 1843.48  4997.6 1841.35  4998.0 1840.85  5002.4 1841.35
  5005.5 1842.99  5020.0 1841.35  5034.6 1842.84  5084.4 1841.55  5140.6 1842.29
  5169.6 1846.26  5184.1 1842.77  5198.4 1841.44  5583.0 1846.66  5723.1 1848.59
  5963.1 1856.40  5984.9 1856.34  6076.3 1858.79  6109.4 1860.65  6169.9 1861.19
#Mann=10,-1,0
  3358.0   0.035       0  4002.2    0.07       0  4020.6   0.035       0
  4813.4    0.07       0  4997.6    0.07       0  5002.4    0.07       0
  5583.0   0.035       0  5963.1    0.07       0  5984.9   0.035       0
  6076.3    0.07       0
Bank Sta=4997.6,5002.4
Exp/Cntr=0.3,0.1

Type RM Length L Ch R = 1,69182,457,457,457
BEGIN DESCRIPTION:
Cat Claw Creek 83.0
END DESCRIPTION:
XS GIS Cut Line= 3
      1570579.11      6810472.77      1572156.36      6810241.36
      1573005.04      6809687.97
#Sta/Elev= 30
  3332.9 1857.94  3379.3 1855.94  3429.8 1856.15  3460.1 1854.62  3601.6 1852.33
  3676.6 1852.39  3783.6 1850.38  3816.2 1850.86  3881.0 1849.12  3975.6 1849.07
  3995.8 1847.97  4278.8 1845.01  4319.2 1843.58  4575.9 1842.33  4676.3 1841.35
  4806.1 1841.05  4876.0 1840.80  4997.6 1839.79  4997.9 1839.29  5002.5 1839.79
  5083.3 1840.87  5413.6 1843.40  5585.6 1846.59  5616.9 1846.35  5715.3 1848.71
  5745.5 1850.54  5845.0 1852.52  5875.3 1854.28  5904.3 1854.27  5940.2 1856.09
#Mann=9,-1,0
  3332.9   0.035       0  4575.9    0.07       0  4676.3   0.035       0
  4806.1    0.07       0  4876.0   0.035       0  4997.6   0.035       0
  5002.5   0.035       0  5083.3    0.07       0  5616.9   0.035       0
Bank Sta=4997.6,5002.5
Exp/Cntr=0.3,0.1

Type RM Length L Ch R = 1,68725,586,586,586
BEGIN DESCRIPTION:
Cat Claw Creek 82.0
END DESCRIPTION:
XS GIS Cut Line= 3
      1571005.00      6811738.00      1572194.04      6810528.34
      1573005.00      6809838.00
#Sta/Elev= 30
  3303.8 1858.32  3374.5 1857.36  3431.0 1854.69  3487.6 1854.39  3600.8 1849.72
  3692.8 1850.50  3749.3 1849.13  3805.9 1849.33  3855.3 1847.72  3947.3 1847.75
  4010.9 1846.47  4244.2 1845.06  4272.5 1845.57  4315.0 1844.16  4463.5 1843.79
  4520.1 1842.33  4661.5 1841.55  4795.8 1838.87  4842.5 1839.04  4997.5 1837.39
  4997.9 1836.89  5002.5 1837.39  5014.6 1839.38  5263.9 1840.33  5596.6 1843.26
  5703.2 1844.59  5752.6 1846.30  5816.3 1846.25  5874.9 1848.31  6065.0 1854.33
#Mann=5,-1,0
  3303.8   0.035       0  4842.5    0.07       0  4997.5    0.07       0
  5002.5    0.07       0  5874.9   0.035       0
Bank Sta=4997.5,5002.5
Exp/Cntr=0.3,0.1

Type RM Length L Ch R = 1,68139,382,382,382
BEGIN DESCRIPTION:
Cat Claw Creek 81.0
END DESCRIPTION:
XS GIS Cut Line= 3
      1571255.00      6812038.00      1572450.76      6810878.39
      1573255.00      6810038.00
#Sta/Elev= 30
  3232.7 1858.11  3282.2 1857.52  3310.5 1855.44  3529.7 1848.96  3650.0 1846.74
  4036.5 1843.63  4293.4 1843.92  4433.3 1841.74  4467.2 1841.45  4781.4 1838.84
  4802.7 1838.12  4823.8 1835.31  4845.1 1837.67  4887.0 1837.44  4944.0 1836.12
  4993.7 1836.87  4997.4 1835.27  4997.8 1834.77  5002.6 1835.27  5007.9 1836.85
  5043.1 1835.66  5134.9 1838.74  5193.9 1838.66  5411.1 1840.57  5474.6 1842.81
  5524.0 1842.26  5695.1 1846.55  5828.1 1851.79  6033.5 1856.66  6061.6 1858.39
#Mann=9,-1,0
  3232.7    0.07       0  4036.5   0.035       0  4433.3    0.07       0
  4467.2   0.035       0  4887.0    0.07       0  4997.4    0.07       0
  5002.6    0.07       0  5193.9   0.035       0  5695.1    0.07       0
Bank Sta=4997.4,5002.6
Exp/Cntr=0.3,0.1

Type RM Length L Ch R = 1,67757,488,488,488
BEGIN DESCRIPTION:
Cat Claw Creek 80.0
END DESCRIPTION:
XS GIS Cut Line= 3
      1571504.98      6812088.01      1572706.18      6811084.84
      1573405.00      6810338.00
#Sta/Elev= 30
  3435.0 1851.67  3499.4 1849.21  3627.0 1846.84  3968.0 1842.48  4124.1 1842.37
  4173.6 1840.63  4350.6 1841.25  4422.2 1840.04  4584.9 1839.78  4659.0 1838.33
  4826.9 1838.43  4949.4 1836.98  4983.1 1836.81  4996.0 1835.98  4997.4 1834.72
  4997.8 1834.22  5002.7 1834.72  5060.7 1836.06  5124.2 1835.11  5337.8 1837.99
  5622.8 1842.21  5711.4 1846.14  5747.0 1846.44  5775.4 1848.44  5854.2 1850.39
  5858.8 1850.58  5944.9 1854.41  5991.8 1854.71  6002.2 1855.24  6022.8 1856.43
#Mann=11,-1,0
  3435.0    0.07       0  4659.0   0.035       0  4949.4    0.07       0
  4997.4    0.07       0  5002.7    0.07       0  5337.8   0.035       0
  5622.8    0.07       0  5854.2   0.035       0  5858.8    0.07       0
  5991.8   0.035       0  6002.2    0.07       0
Bank Sta=4997.4,5002.7
Exp/Cntr=0.3,0.1

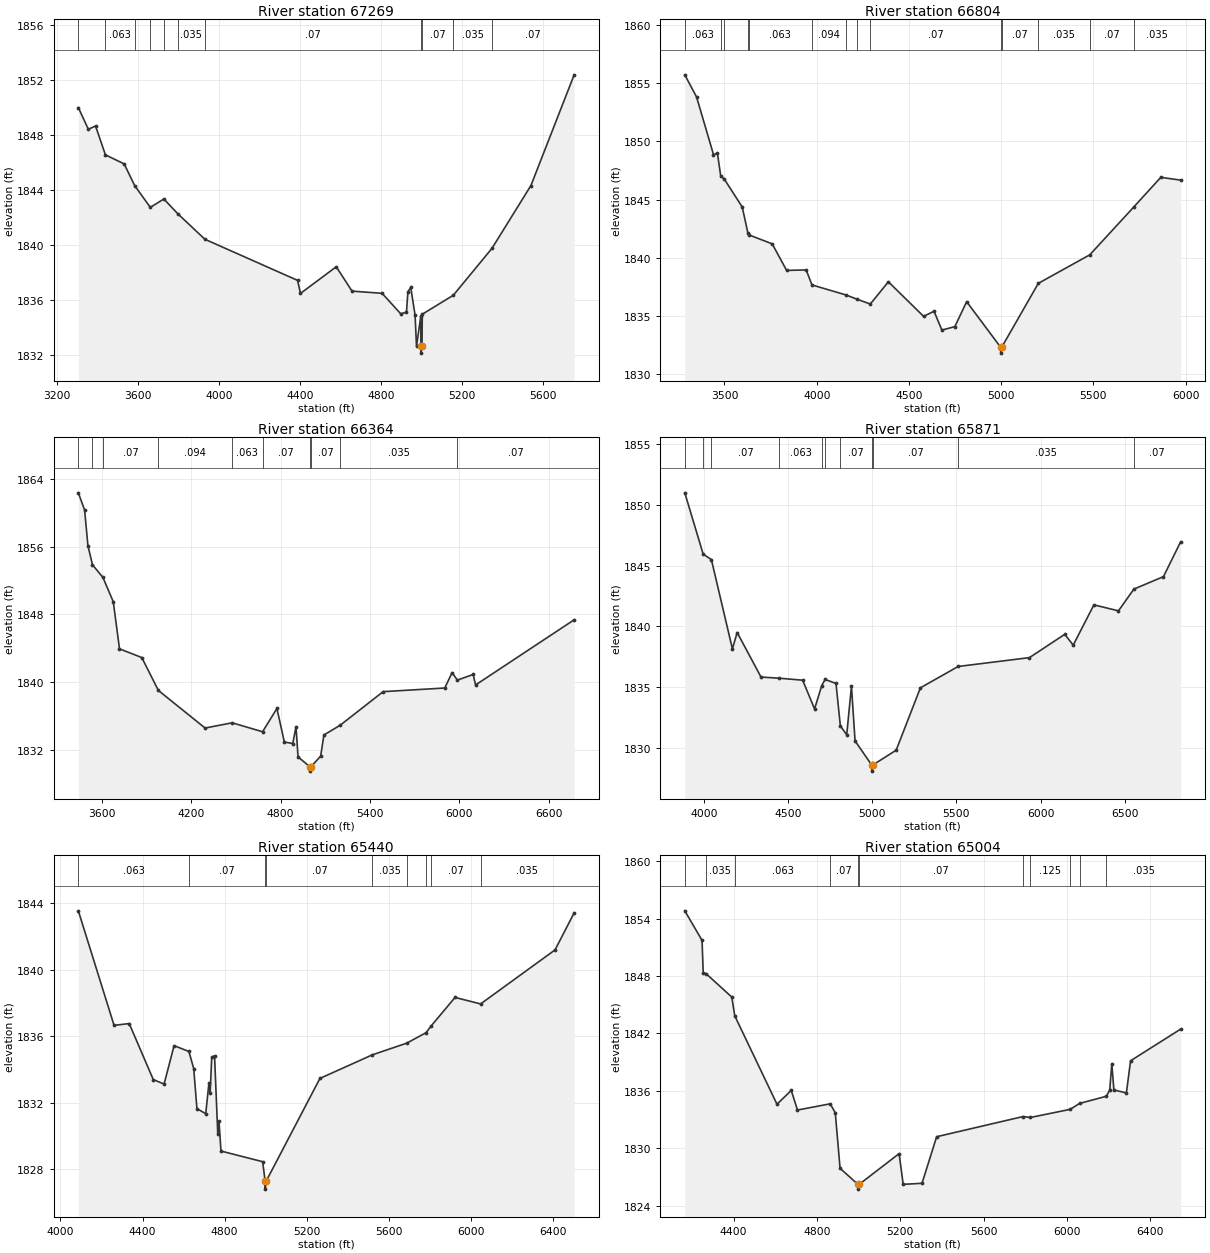
Type RM Length L Ch R = 1,67269,465,465,465
BEGIN DESCRIPTION:
Cat Claw Creek 79.0
END DESCRIPTION:
XS GIS Cut Line= 3
      1571854.97      6812438.03      1573051.14      6811239.66
      1573504.97      6810638.04
#Sta/Elev= 30
  3306.8 1850.02  3356.3 1848.44  3391.7 1848.68  3440.5 1846.58  3533.1 1845.92
  3584.6 1844.35  3662.0 1842.76  3728.8 1843.37  3796.7 1842.31  3931.4 1840.44
  4388.7 1837.45  4402.9 1836.50  4579.6 1838.44  4657.4 1836.67  4805.9 1836.51
  4897.8 1835.02  4926.1 1835.14  4933.2 1836.62  4947.3 1836.94  4968.6 1834.92
  4975.6 1832.66  4996.8 1834.85  4997.4 1832.66  4997.8 1832.16  5002.7 1832.66
  5004.2 1834.99  5157.3 1836.37  5348.0 1839.78  5540.3 1844.35  5753.6 1852.40
#Mann=11,-1,0
  3306.8    0.07       0  3440.5   0.063       0  3584.6   0.094       0
  3662.0   0.035       0  3728.8   0.094       0  3796.7   0.035       0
  3931.4    0.07       0  4997.4    0.07       0  5002.7    0.07       0
  5157.3   0.035       0  5348.0    0.07       0
Bank Sta=4997.4,5002.7
Exp/Cntr=0.3,0.1

Type RM Length L Ch R = 1,66804,440,440,440
BEGIN DESCRIPTION:
Cat Claw Creek 78.0
END DESCRIPTION:
XS GIS Cut Line= 4
      1572104.99      6812738.01      1573241.55      6811544.01
      1573373.39      6811507.77      1573812.09      6810718.94
#Sta/Elev= 30
  3285.0 1855.73  3348.7 1853.83  3440.5 1848.88  3462.0 1848.98  3479.7 1847.04
  3499.8 1846.75  3596.3 1844.37  3627.6 1842.10  3631.6 1841.98  3758.9 1841.20
  3836.9 1838.92  3942.9 1838.96  3974.6 1837.67  4158.8 1836.81  4219.3 1836.44
  4290.6 1836.03  4388.6 1837.94  4579.5 1834.97  4636.1 1835.41  4678.6 1833.79
  4749.0 1834.09  4812.9 1836.23  4997.4 1832.31  4997.8 1831.81  5002.7 1832.31
  5201.5 1837.81  5480.4 1840.26  5720.6 1844.40  5865.4 1846.92  5972.8 1846.68
#Mann=14,-1,0
  3285.0   0.063       0  3479.7   0.035       0  3499.8   0.063       0
  3627.6   0.035       0  3631.6   0.063       0  3974.6   0.094       0
  4158.8   0.063       0  4219.3   0.094       0  4290.6    0.07       0
  4997.4    0.07       0  5002.7    0.07       0  5201.5   0.035       0
  5480.4    0.07       0  5720.6   0.035       0
Bank Sta=4997.4,5002.7
Exp/Cntr=0.3,0.1

Type RM Length L Ch R = 1,66364,493,493,493
BEGIN DESCRIPTION:
Cat Claw Creek 77.0
END DESCRIPTION:
XS GIS Cut Line= 3
      1572204.97      6812938.03      1573398.88      6811935.82
      1574955.01      6811087.99
#Sta/Elev= 30
  3441.2 1862.35  3483.5 1860.31  3505.6 1856.11  3536.3 1853.85  3606.6 1852.35
  3676.0 1849.48  3717.7 1843.92  3867.3 1842.89  3979.0 1839.00  4292.7 1834.56
  4475.0 1835.18  4678.8 1834.12  4775.3 1836.87  4825.2 1832.91  4882.0 1832.73
  4903.5 1834.72  4917.1 1831.16  4997.1 1829.97  4997.6 1829.47  5003.0 1829.97
  5069.1 1831.24  5090.9 1833.74  5199.5 1834.88  5488.8 1838.86  5902.8 1839.29
  5952.2 1841.11  5987.5 1840.22  6093.6 1840.89  6109.8 1839.65  6772.1 1847.35
#Mann=10,-1,0
  3441.2   0.063       0  3536.3   0.035       0  3606.6    0.07       0
  3979.0   0.094       0  4475.0   0.063       0  4678.8    0.07       0
  4997.1    0.07       0  5003.0    0.07       0  5199.5   0.035       0
  5987.5    0.07       0
Bank Sta=4997.1,5003
Exp/Cntr=0.3,0.1

Type RM Length L Ch R = 1,65871,431,431,431
BEGIN DESCRIPTION:
Cat Claw Creek 76.0
END DESCRIPTION:
XS GIS Cut Line= 3
      1572655.02      6813187.98      1573454.50      6812413.21
      1575005.01      6811437.99
#Sta/Elev= 30
  3886.7 1851.01  3995.7 1845.96  4044.7 1845.50  4169.5 1838.14  4197.8 1839.49
  4339.3 1835.82  4449.1 1835.72  4586.7 1835.56  4657.5 1833.19  4700.1 1835.11
  4720.0 1835.62  4784.8 1835.29  4810.6 1831.79  4848.4 1831.06  4876.6 1835.06
  4898.0 1830.55  4997.1 1828.56  4997.6 1828.06  5003.0 1828.56  5142.3 1829.79
  5286.1 1834.93  5510.3 1836.69  5933.7 1837.42  6143.4 1839.34  6193.8 1838.45
  6316.5 1841.77  6462.5 1841.28  6554.0 1843.07  6729.8 1844.10  6831.7 1846.97
#Mann=11,-1,0
  3886.7   0.094       0  3995.7   0.063       0  4044.7    0.07       0
  4449.1   0.063       0  4700.1   0.094       0  4720.0   0.063       0
  4810.6    0.07       0  4997.1    0.07       0  5003.0    0.07       0
  5510.3   0.035       0  6554.0    0.07       0
Bank Sta=4997.1,5003
Exp/Cntr=0.3,0.1

Type RM Length L Ch R = 1,65440,436,436,436
BEGIN DESCRIPTION:
Cat Claw Creek 75.0
END DESCRIPTION:
XS GIS Cut Line= 3
      1572904.98      6813188.01      1573691.68      6812724.67
      1574905.02      6811837.99
#Sta/Elev= 30
  4087.0 1843.53  4261.1 1836.64  4334.9 1836.75  4452.1 1833.38  4504.8 1833.11
  4553.6 1835.42  4625.8 1835.07  4649.2 1834.04  4664.9 1831.63  4707.8 1831.33
  4723.5 1833.19  4729.3 1832.58  4736.9 1834.72  4750.7 1834.81  4766.4 1830.10
  4772.2 1830.90  4782.0 1829.08  4985.0 1828.44  4997.0 1827.29  4997.5 1826.79
  5003.0 1827.29  5264.2 1833.45  5520.0 1834.87  5687.0 1835.57  5781.2 1836.20
  5805.0 1836.59  5922.4 1838.32  6047.0 1837.93  6409.7 1841.18  6502.8 1843.41
#Mann=9,-1,0
  4087.0   0.063       0  4625.8    0.07       0  4997.0    0.07       0
  5003.0    0.07       0  5520.0   0.035       0  5687.0    0.07       0
  5781.2   0.035       0  5805.0    0.07       0  6047.0   0.035       0
Bank Sta=4997,5003
Exp/Cntr=0.3,0.1

Type RM Length L Ch R = 1,65004,336,336,336
BEGIN DESCRIPTION:
Cat Claw Creek 74.0
END DESCRIPTION:
XS GIS Cut Line= 3
      1572754.99      6813438.01      1573510.54      6813085.58
      1575055.05      6813138.00
#Sta/Elev= 30
  4166.3 1854.82  4249.1 1851.73  4254.6 1848.36  4268.4 1848.25  4391.8 1845.80
  4406.1 1843.84  4608.6 1834.60  4677.2 1836.04  4707.0 1833.99  4864.0 1834.64
  4888.4 1833.70  4911.3 1827.90  4996.9 1826.22  4997.4 1825.72  5003.1 1826.22
  5194.6 1829.43  5214.2 1826.22  5304.6 1826.33  5374.7 1831.20  5789.6 1833.31
  5823.9 1833.21  6015.1 1834.06  6060.4 1834.68  6189.1 1835.43  6205.2 1836.09
  6215.2 1838.83  6225.2 1836.09  6285.2 1835.78  6305.2 1839.14  6545.4 1842.45
#Mann=11,-1,0
  4166.3   0.063       0  4268.4   0.035       0  4406.1   0.063       0
  4864.0    0.07       0  4996.9    0.07       0  5003.1    0.07       0
  5789.6   0.094       0  5823.9   0.125       0  6015.1   0.094       0
  6060.4   0.125       0  6189.1   0.035       0
Bank Sta=4996.9,5003.1
Exp/Cntr=0.3,0.1

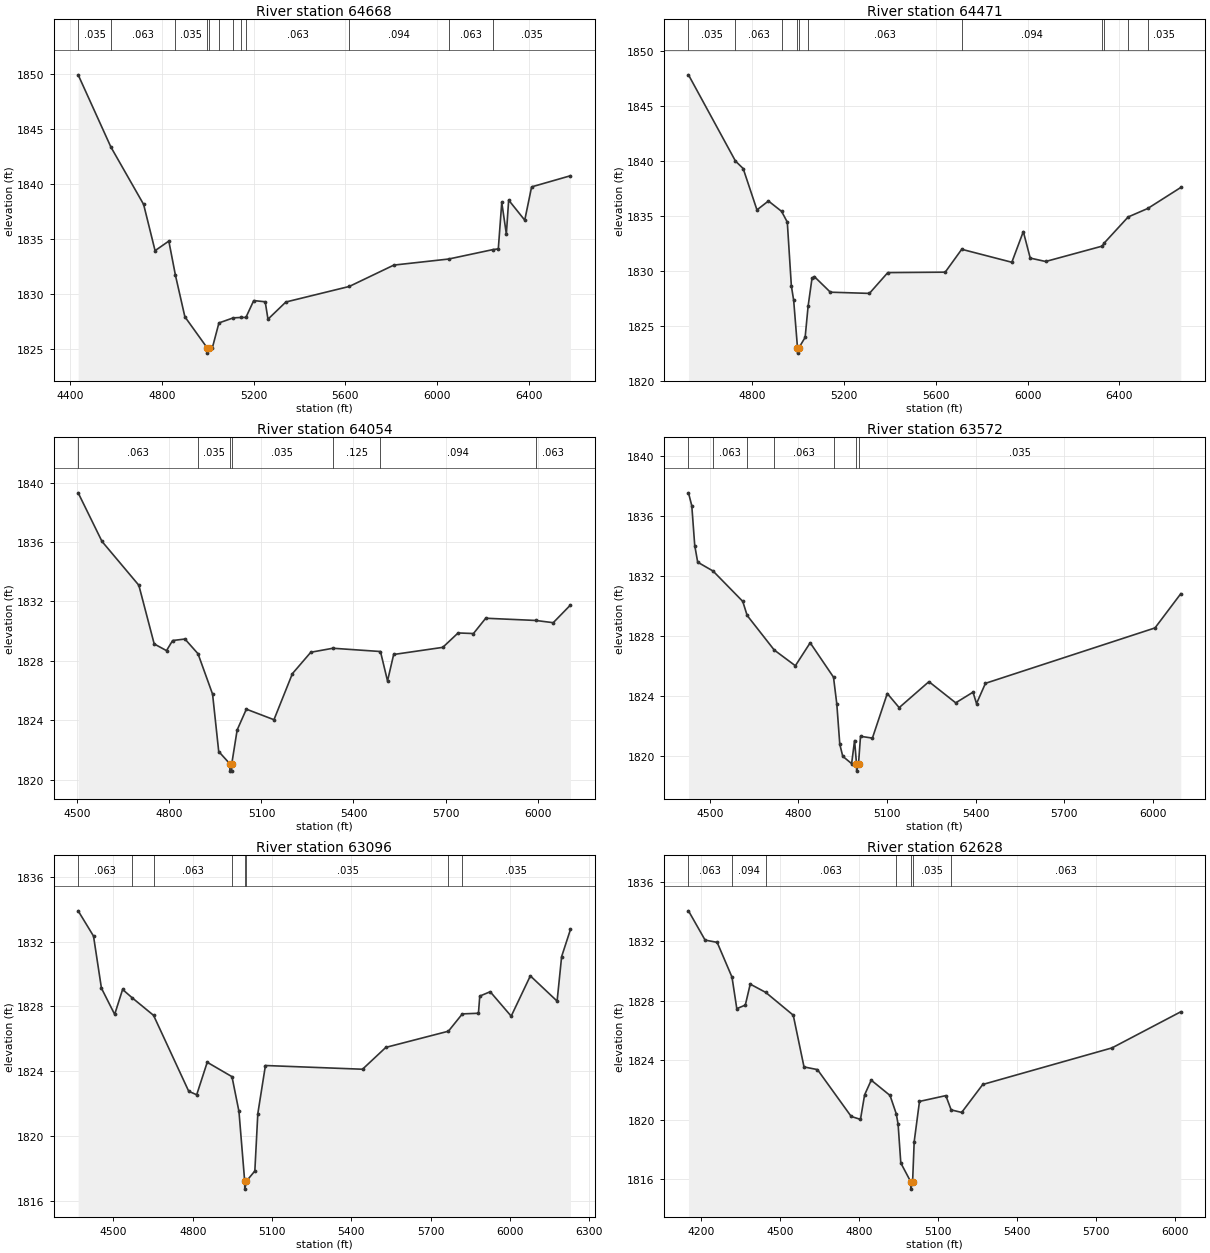
Type RM Length L Ch R = 1,64668,197,197,197
BEGIN DESCRIPTION:
Cat Claw Creek 73.2
END DESCRIPTION:
XS GIS Cut Line= 3
      1572889.68      6813422.58      1573576.49      6813401.22
      1575034.16      6813314.25
#Sta/Elev= 30
  4434.7 1849.88  4577.4 1843.33  4720.2 1838.12  4770.2 1833.92  4830.2 1834.79
  4859.2 1831.67  4900.2 1827.92  4996.7 1825.12  4997.2 1824.62  5003.3 1825.12
  5020.3 1825.12  5048.7 1827.36  5111.2 1827.82  5146.8 1827.86  5166.4 1827.86
  5200.5 1829.39  5250.6 1829.28  5262.7 1827.70  5340.7 1829.26  5617.1 1830.67
  5811.6 1832.61  6050.5 1833.16  6244.5 1834.02  6267.3 1834.08  6282.4 1838.30
  6302.4 1835.43  6312.5 1838.51  6382.6 1836.69  6412.6 1839.71  6582.1 1840.72
#Mann=12,-1,0
  4434.7   0.035       0  4577.4   0.063       0  4859.2   0.035       0
  4996.7   0.035       0  5003.3   0.035       0  5048.7   0.063       0
  5111.2   0.035       0  5146.8    0.07       0  5166.4   0.063       0
  5617.1   0.094       0  6050.5   0.063       0  6244.5   0.035       0
Bank Sta=4996.7,5003.3
Exp/Cntr=0.3,0.1

Type RM Length L Ch R = 1,64471,417,417,417
BEGIN DESCRIPTION:
Cat Claw Creek 73.0
END DESCRIPTION:
XS GIS Cut Line= 3
      1572976.57      6813616.30      1573663.35      6813594.95
      1575120.45      6813508.02
#Sta/Elev= 30
  4521.4 1847.80  4726.3 1839.96  4759.9 1839.28  4820.0 1835.52  4870.0 1836.33
  4927.3 1835.39  4952.3 1834.41  4970.0 1828.61  4980.1 1827.30  4996.7 1823.00
  4997.2 1822.50  5003.3 1823.00  5030.1 1823.93  5043.0 1826.76  5060.1 1829.31
  5070.1 1829.46  5140.1 1828.04  5310.3 1827.93  5390.5 1829.82  5640.9 1829.86
  5712.9 1831.94  5931.4 1830.76  5981.5 1833.55  6011.6 1831.14  6078.8 1830.83
  6325.7 1832.23  6333.9 1832.50  6438.7 1834.88  6524.1 1835.65  6668.2 1837.56
#Mann=11,-1,0
  4521.4   0.035       0  4726.3   0.063       0  4927.3   0.035       0
  4996.7   0.035       0  5003.3   0.035       0  5043.0   0.063       0
  5712.9   0.094       0  6325.7   0.063       0  6333.9   0.035       0
  6438.7   0.063       0  6524.1   0.035       0
Bank Sta=4996.7,5003.3
Exp/Cntr=0.3,0.1

Type RM Length L Ch R = 1,64054,482,482,482
BEGIN DESCRIPTION:
Cat Claw Creek 72.0
END DESCRIPTION:
XS GIS Cut Line= 3
      1573197.45      6813955.57      1573694.21      6813928.33
      1574801.17      6813897.13
#Sta/Elev= 30
  4502.5 1839.31  4580.2 1836.04  4700.3 1833.09  4750.4 1829.14  4790.5 1828.69
  4810.5 1829.37  4850.6 1829.47  4893.2 1828.48  4940.7 1825.76  4960.7 1821.90
  4996.7 1821.08  4997.2 1820.58  5002.8 1820.58  5003.3 1821.08  5020.8 1823.35
  5050.8 1824.75  5140.8 1824.04  5200.9 1827.14  5260.9 1828.58  5332.9 1828.85
  5488.0 1828.63  5511.0 1826.65  5531.0 1828.43  5691.1 1828.91  5741.1 1829.88
  5791.1 1829.84  5831.1 1830.87  5994.3 1830.72  6051.2 1830.57  6107.4 1831.76
#Mann=7,-1,0
  4502.5   0.063       0  4893.2   0.035       0  4996.7   0.035       0
  5003.3   0.035       0  5332.9   0.125       0  5488.0   0.094       0
  5994.3   0.063       0
Bank Sta=4996.7,5003.3
Exp/Cntr=0.3,0.1

Type RM Length L Ch R = 1,63572,476,476,476
BEGIN DESCRIPTION:
Cat Claw Creek 71.0
END DESCRIPTION:
XS GIS Cut Line= 3
      1573183.85      6814349.63      1573754.88      6814391.96
      1574841.72      6814256.08
#Sta/Elev= 30
  4427.4 1837.53  4438.6 1836.67  4448.6 1834.02  4458.6 1832.91  4510.7 1832.32
  4611.2 1830.30  4626.2 1829.36  4717.8 1827.06  4789.5 1826.01  4839.7 1827.54
  4918.7 1825.25  4929.9 1823.46  4940.0 1820.78  4950.0 1819.98  4980.1 1819.49
  4990.1 1821.03  4996.6 1819.49  4997.1 1818.99  5003.5 1819.49  5010.2 1821.31
  5050.5 1821.19  5100.9 1824.16  5141.2 1823.22  5242.0 1824.95  5332.7 1823.54
  5391.4 1824.25  5403.2 1823.49  5433.5 1824.84  6007.9 1828.53  6095.3 1830.81
#Mann=7,-1,0
  4427.4   0.035       0  4510.7   0.063       0  4626.2   0.094       0
  4717.8   0.063       0  4918.7   0.035       0  4996.6   0.035       0
  5003.5   0.035       0
Bank Sta=4996.6,5003.5
Exp/Cntr=0.3,0.1

Type RM Length L Ch R = 1,63096,468,468,468
BEGIN DESCRIPTION:
Cat Claw Creek 70.0
END DESCRIPTION:
XS GIS Cut Line= 3
      1573156.97      6814852.08      1573858.32      6814821.90
      1575004.97      6814638.01
#Sta/Elev= 30
  4366.4 1833.91  4424.5 1832.35  4454.5 1829.13  4504.6 1827.51  4534.6 1829.05
  4571.2 1828.53  4651.8 1827.45  4784.8 1822.76  4815.0 1822.54  4854.9 1824.55
  4948.6 1823.66  4975.0 1821.51  4996.6 1817.21  4997.1 1816.71  5003.5 1817.21
  5035.1 1817.83  5046.4 1821.38  5075.2 1824.35  5442.6 1824.12  5530.9 1825.47
  5767.7 1826.47  5820.4 1827.54  5881.4 1827.58  5886.4 1828.64  5925.9 1828.91
  6005.3 1827.40  6077.8 1829.89  6179.1 1828.33  6196.2 1831.08  6229.7 1832.76
#Mann=8,-1,0
  4366.4   0.063       0  4571.2   0.094       0  4651.8   0.063       0
  4948.6   0.035       0  4996.6   0.035       0  5003.5   0.035       0
  5767.7   0.063       0  5820.4   0.035       0
Bank Sta=4996.6,5003.5
Exp/Cntr=0.3,0.1

Type RM Length L Ch R = 1,62628,382,382,382
BEGIN DESCRIPTION:
Cat Claw Creek 69.0
END DESCRIPTION:
XS GIS Cut Line= 3
      1573075.29      6815091.14      1573905.36      6815258.15
      1574925.84      6815293.73
#Sta/Elev= 30
  4153.3 1834.04  4216.4 1832.07  4262.1 1831.92  4318.4 1829.58  4336.6 1827.46
  4368.9 1827.70  4387.6 1829.11  4446.6 1828.55  4550.8 1827.02  4591.6 1823.54
  4642.6 1823.36  4770.6 1820.21  4805.8 1820.01  4821.5 1821.66  4846.6 1822.65
  4918.0 1821.62  4941.5 1820.39  4948.6 1819.68  4958.8 1817.08  4996.4 1815.82
  4996.9 1815.32  5003.6 1815.82  5009.6 1818.51  5029.7 1821.22  5129.7 1821.61
  5149.8 1820.65  5189.8 1820.48  5269.8 1822.36  5760.1 1824.82  6021.1 1827.25
#Mann=7,-1,0
  4153.3   0.063       0  4318.4   0.094       0  4446.6   0.063       0
  4941.5   0.035       0  4996.4   0.035       0  5003.6   0.035       0
  5149.8   0.063       0
Bank Sta=4996.4,5003.6
Exp/Cntr=0.3,0.1