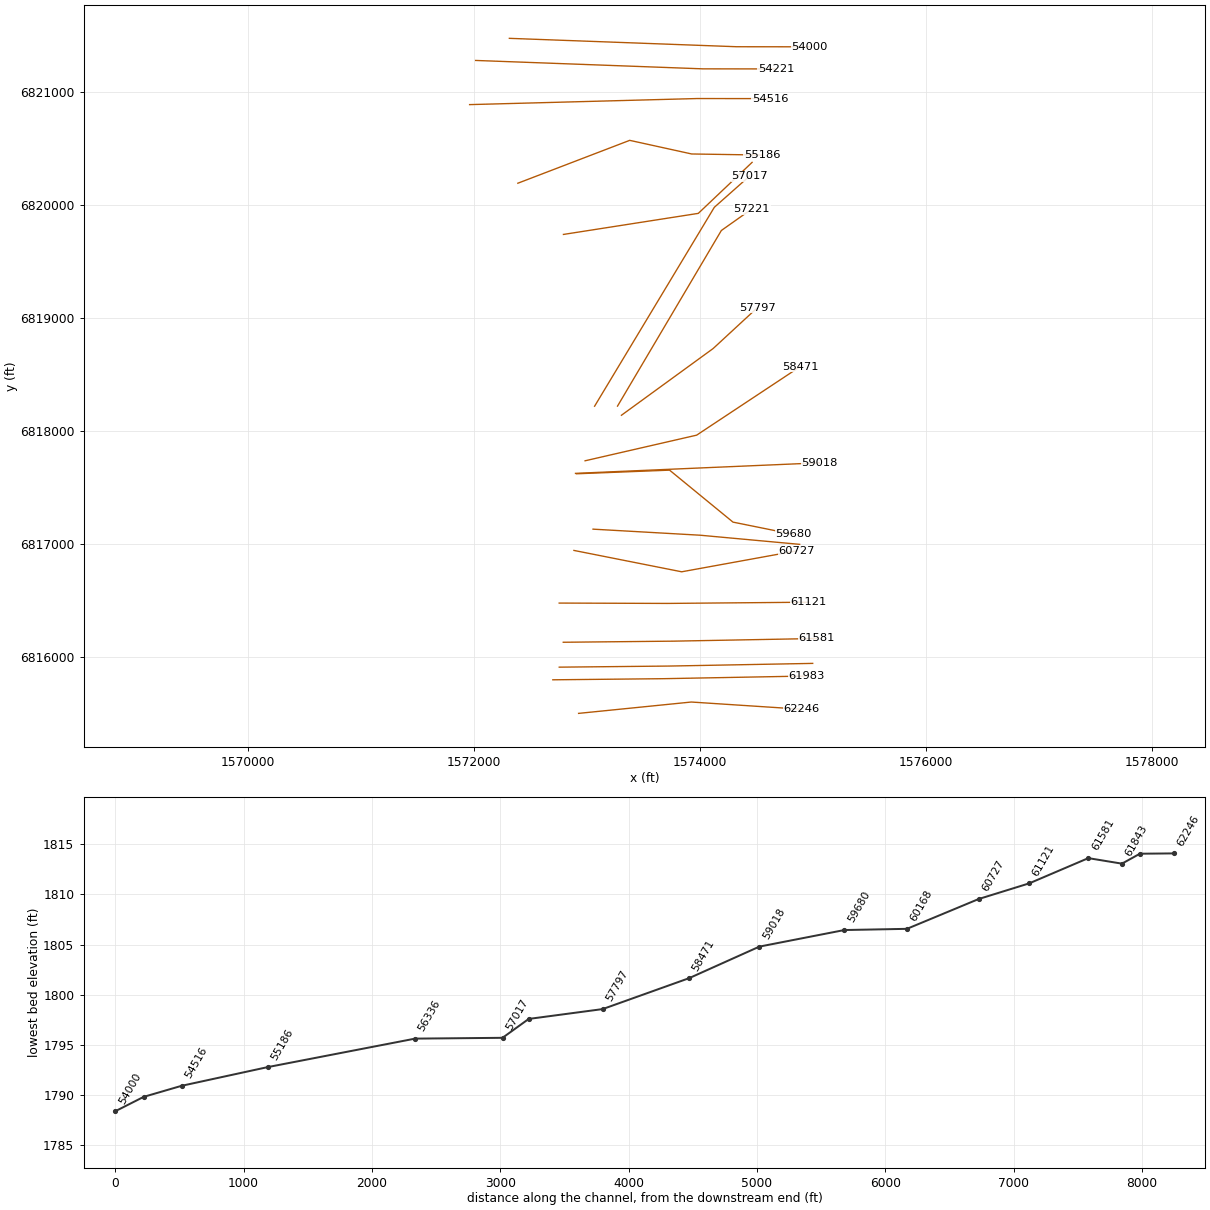
HEC-RAS study Cat Claw Creek.prj: Cat Claw Creek Base Level Engineering

--- Cat Claw Creek.g01 (geometry) --- (continued)

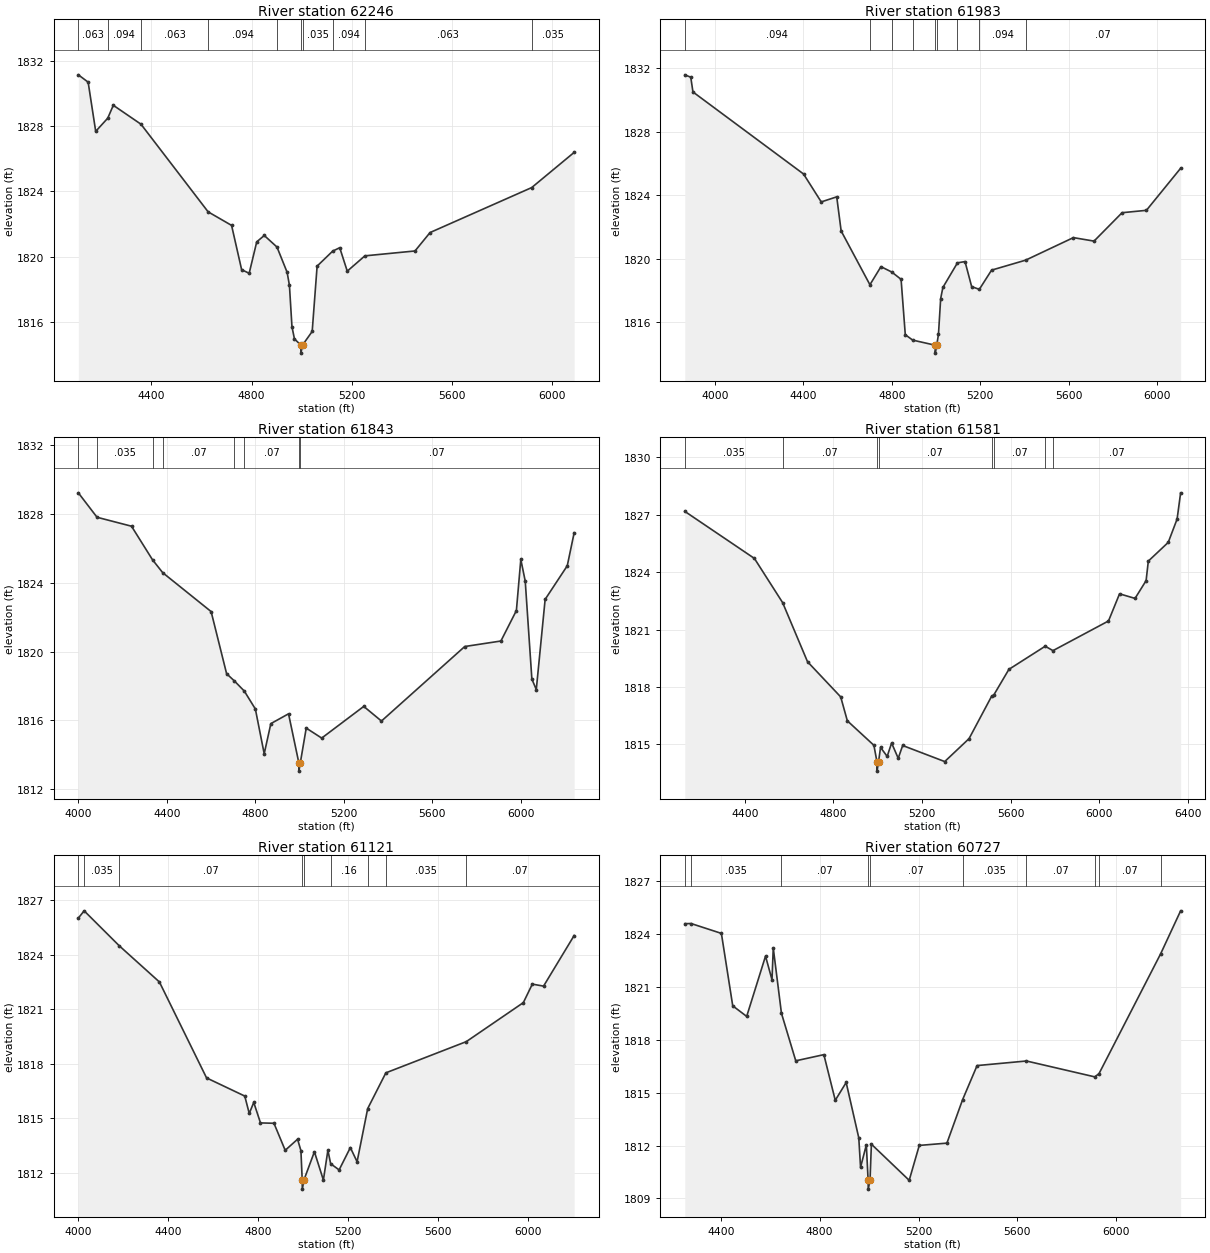
Type RM Length L Ch R = 1,62246,263,263,263
BEGIN DESCRIPTION:
Cat Claw Creek 68.0
END DESCRIPTION:
XS GIS Cut Line= 3
      1572926.00      6815499.85      1573922.90      6815600.26
      1574899.37      6815536.45
#Sta/Elev= 30
  4107.9 1831.15  4147.1 1830.70  4177.3 1827.68  4225.4 1828.49  4247.6 1829.28
  4358.1 1828.12  4626.4 1822.74  4720.0 1821.91  4760.2 1819.19  4790.3 1818.97
  4820.5 1820.90  4850.6 1821.29  4901.4 1820.58  4941.9 1819.03  4951.1 1818.23
  4961.2 1815.69  4971.2 1814.94  4996.4 1814.57  4996.9 1814.07  5003.6 1814.57
  5042.0 1815.40  5061.7 1819.41  5123.8 1820.33  5152.0 1820.54  5182.1 1819.10
  5252.5 1820.04  5452.7 1820.34  5512.8 1821.47  5918.8 1824.23  6088.4 1826.39
#Mann=10,-1,0
  4107.9   0.063       0  4225.4   0.094       0  4358.1   0.063       0
  4626.4   0.094       0  4901.4   0.035       0  4996.4   0.035       0
  5003.6   0.035       0  5123.8   0.094       0  5252.5   0.063       0
  5918.8   0.035       0
Bank Sta=4996.4,5003.6
Exp/Cntr=0.3,0.1

Type RM Length L Ch R = 1,61983,140,140,140
BEGIN DESCRIPTION:
Cat Claw Creek 67.4
END DESCRIPTION:
XS GIS Cut Line= 3
      1572698.14      6815796.98      1573671.91      6815806.75
      1574939.68      6815830.30
#Sta/Elev= 30
  3864.5 1831.58  3891.4 1831.43  3901.4 1830.50  4401.4 1825.33  4481.4 1823.57
  4551.4 1823.89  4571.4 1821.74  4701.5 1818.35  4751.4 1819.49  4800.4 1819.15
  4842.4 1818.69  4861.4 1815.20  4895.0 1814.86  4996.4 1814.54  4996.9 1814.04
  5003.6 1814.54  5011.4 1815.22  5021.4 1817.48  5031.4 1818.18  5097.3 1819.73
  5131.5 1819.81  5161.5 1818.23  5196.2 1818.06  5251.5 1819.27  5405.6 1819.90
  5621.5 1821.32  5714.8 1821.10  5841.6 1822.89  5951.6 1823.04  6106.3 1825.69
#Mann=9,-1,0
  3864.5   0.094       0  4701.5   0.063       0  4800.4   0.035       0
  4895.0    0.07       0  4996.4    0.07       0  5003.6    0.07       0
  5097.3   0.035       0  5196.2   0.094       0  5405.6    0.07       0
Bank Sta=4996.4,5003.6
Exp/Cntr=0.3,0.1

Type RM Length L Ch R = 1,61843,262,262,262
BEGIN DESCRIPTION:
Cat Claw Creek 67.2
END DESCRIPTION:
XS GIS Cut Line= 3
      1572754.65      6815908.83      1573728.38      6815918.61
      1574996.18      6815942.16
#Sta/Elev= 30
  3999.7 1829.22  4084.3 1827.80  4240.1 1827.28  4335.1 1825.33  4381.2 1824.58
  4600.1 1822.32  4670.1 1818.71  4705.3 1818.29  4750.2 1817.70  4800.1 1816.66
  4840.1 1814.06  4870.1 1815.81  4950.1 1816.38  4996.4 1813.55  4996.9 1813.05
  5003.6 1813.55  5030.1 1815.55  5100.1 1814.97  5290.2 1816.81  5370.2 1815.96
  5746.8 1820.29  5910.3 1820.61  5980.3 1822.38  6000.3 1825.35  6020.3 1824.09
  6050.3 1818.40  6070.3 1817.79  6110.3 1823.03  6210.3 1824.98  6241.5 1826.90
#Mann=8,-1,0
  3999.7   0.063       0  4084.3   0.035       0  4335.1   0.094       0
  4381.2    0.07       0  4705.3   0.063       0  4750.2    0.07       0
  4996.4    0.07       0  5003.6    0.07       0
Bank Sta=4996.4,5003.6
Exp/Cntr=0.3,0.1

Type RM Length L Ch R = 1,61581,460,460,460
BEGIN DESCRIPTION:
Cat Claw Creek 67.0
END DESCRIPTION:
XS GIS Cut Line= 3
      1572790.40      6816129.15      1573764.12      6816138.93
      1575030.93      6816162.47
#Sta/Elev= 30
  4128.0 1827.18  4442.6 1824.72  4570.1 1822.41  4682.6 1819.32  4832.6 1817.48
  4862.6 1816.23  4982.6 1814.95  4996.3 1814.10  4996.8 1813.60  5003.8 1814.10
  5012.6 1814.84  5042.6 1814.37  5062.6 1815.07  5092.6 1814.27  5112.6 1814.94
  5302.7 1814.10  5412.7 1815.30  5514.4 1817.51  5524.4 1817.58  5592.7 1818.92
  5756.8 1820.13  5792.0 1819.90  6042.8 1821.45  6092.8 1822.87  6162.8 1822.63
  6212.8 1823.56  6222.8 1824.58  6312.9 1825.56  6352.9 1826.78  6368.8 1828.15
#Mann=8,-1,0
  4128.0   0.035       0  4570.1    0.07       0  4996.3    0.07       0
  5003.8    0.07       0  5514.4   0.035       0  5524.4    0.07       0
  5756.8   0.035       0  5792.0    0.07       0
Bank Sta=4996.3,5003.8
Exp/Cntr=0.3,0.1

Type RM Length L Ch R = 1,61121,394,394,394
BEGIN DESCRIPTION:
Cat Claw Creek 66.0
END DESCRIPTION:
XS GIS Cut Line= 3
      1572754.25      6816475.88      1573713.08      6816472.85
      1574961.20      6816483.63
#Sta/Elev= 30
  3999.7 1826.03  4025.6 1826.43  4182.1 1824.50  4360.5 1822.51  4570.5 1817.22
  4740.5 1816.22  4760.5 1815.26  4780.5 1815.87  4810.5 1814.74  4870.5 1814.72
  4920.5 1813.23  4975.5 1813.84  4990.5 1813.21  4996.2 1811.59  4996.7 1811.09
  5003.8 1811.59  5050.5 1813.15  5090.5 1811.59  5110.5 1813.23  5122.8 1812.49
  5160.5 1812.15  5210.5 1813.38  5240.5 1812.60  5287.7 1815.53  5368.6 1817.50
  5726.6 1819.22  5980.5 1821.37  6020.5 1822.39  6070.5 1822.28  6206.7 1825.07
#Mann=9,-1,0
  3999.7    0.07       0  4025.6   0.035       0  4182.1    0.07       0
  4996.2    0.07       0  5003.8    0.07       0  5122.8    0.16       0
  5287.7    0.07       0  5368.6   0.035       0  5726.6    0.07       0
Bank Sta=4996.2,5003.8
Exp/Cntr=0.3,0.1

Type RM Length L Ch R = 1,60727,559,559,559
BEGIN DESCRIPTION:
Cat Claw Creek 65.0
END DESCRIPTION:
XS GIS Cut Line= 3
      1572884.78      6816941.78      1573837.72      6816752.69
      1574854.96      6816937.99
#Sta/Elev= 30
  4254.7 1824.59  4279.9 1824.60  4402.7 1824.04  4448.6 1819.93  4505.0 1819.33
  4581.2 1822.75  4607.4 1821.41  4612.5 1823.21  4645.6 1819.51  4703.5 1816.81
  4817.2 1817.16  4863.3 1814.57  4907.4 1815.58  4958.4 1812.44  4965.6 1810.77
  4989.0 1812.04  4996.2 1810.03  4996.7 1809.53  5003.9 1810.03  5009.4 1812.08
  5162.3 1810.03  5203.1 1812.01  5314.9 1812.14  5378.2 1814.60  5436.9 1816.54
  5636.6 1816.80  5912.8 1815.90  5930.0 1816.08  6179.7 1822.89  6260.2 1825.32
#Mann=10,-1,0
  4254.7   0.094       0  4279.9   0.035       0  4645.6    0.07       0
  4996.2    0.07       0  5003.9    0.07       0  5378.2   0.035       0
  5636.6    0.07       0  5912.8   0.035       0  5930.0    0.07       0
  6179.7   0.035       0
Bank Sta=4996.2,5003.9
Exp/Cntr=0.3,0.1

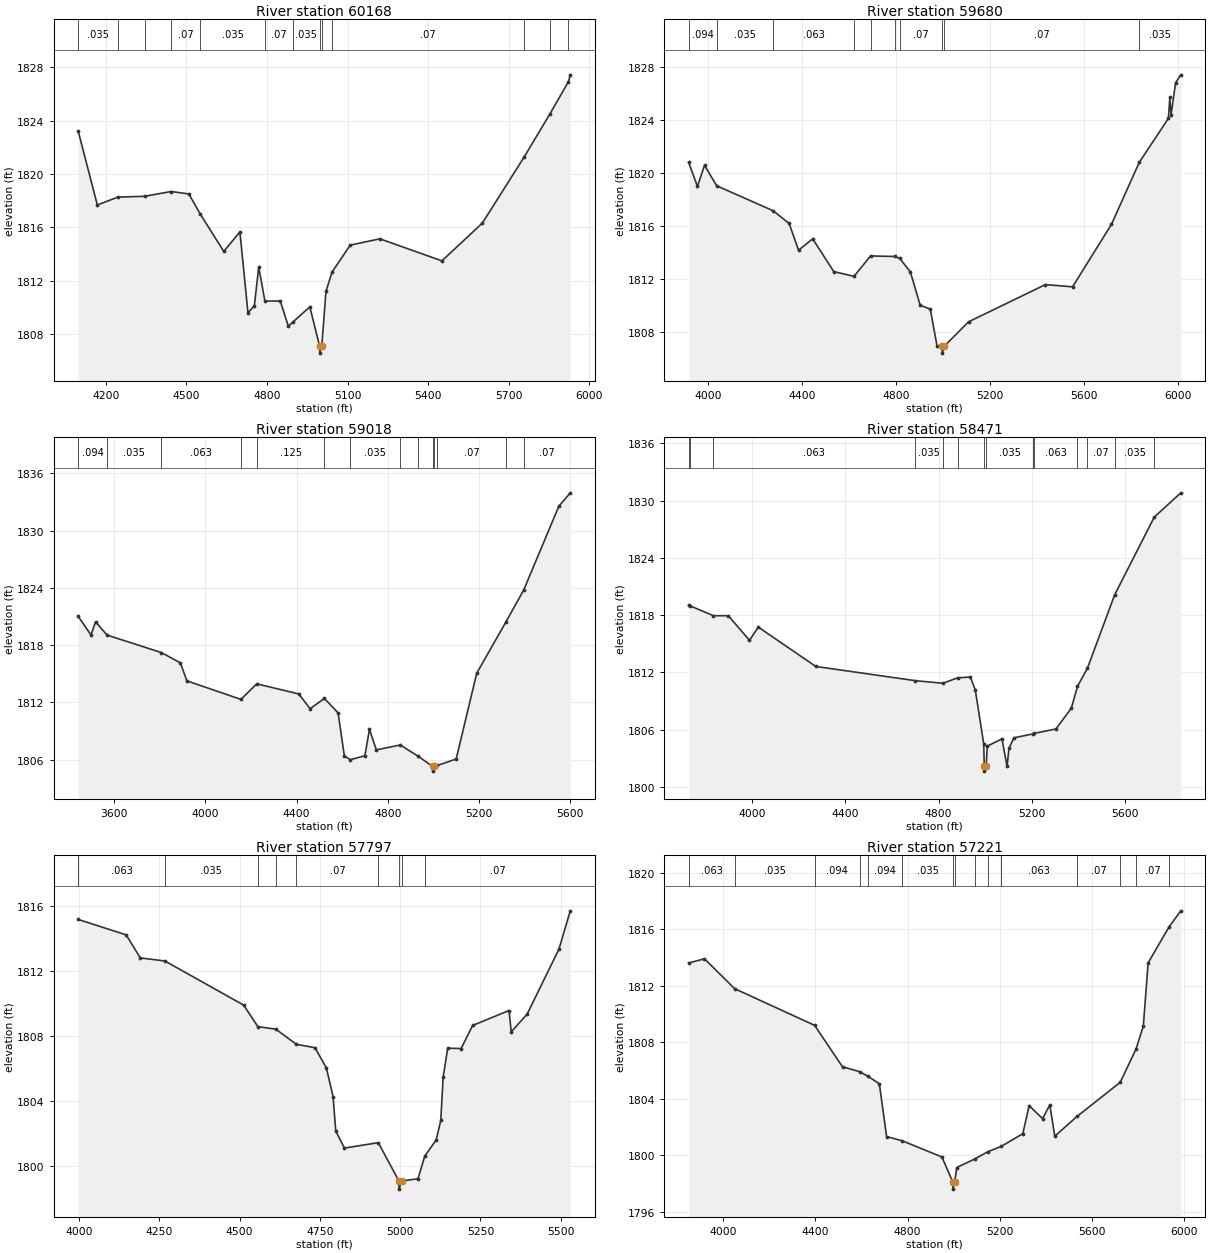
Type RM Length L Ch R = 1,60168,488,488,488
BEGIN DESCRIPTION:
Cat Claw Creek 64.0
END DESCRIPTION:
XS GIS Cut Line= 3
      1573053.60      6817130.05      1574000.88      6817076.37
      1574881.17      6816995.52
#Sta/Elev= 30
  4096.7 1823.22  4168.2 1817.67  4244.6 1818.26  4343.9 1818.32  4443.2 1818.68
  4508.8 1818.50  4551.1 1817.00  4639.0 1814.19  4699.1 1815.65  4729.1 1809.58
  4752.9 1810.11  4769.2 1813.02  4792.2 1810.46  4849.3 1810.47  4879.4 1808.59
  4895.2 1808.87  4959.5 1810.03  4996.1 1807.06  4996.6 1806.56  5003.9 1807.06
  5019.6 1811.19  5042.1 1812.63  5109.9 1814.66  5220.4 1815.13  5451.3 1813.48
  5602.0 1816.31  5757.7 1821.27  5852.8 1824.47  5922.6 1826.92  5929.5 1827.43
#Mann=13,-1,0
  4096.7   0.035       0  4244.6   0.063       0  4343.9   0.094       0
  4443.2    0.07       0  4551.1   0.035       0  4792.2    0.07       0
  4895.2   0.035       0  4996.1   0.035       0  5003.9   0.035       0
  5042.1    0.07       0  5757.7   0.035       0  5852.8    0.07       0
  5922.6   0.035       0
Bank Sta=4996.1,5003.9
Exp/Cntr=0.3,0.1

Type RM Length L Ch R = 1,59680,662,662,662
BEGIN DESCRIPTION:
Cat Claw Creek 63.0
END DESCRIPTION:
XS GIS Cut Line= 4
      1572907.53      6817620.04      1573730.65      6817652.16
      1574291.45      6817192.26      1574826.68      6817083.91
#Sta/Elev= 30
  3917.0 1820.82  3954.5 1819.01  3984.5 1820.61  4036.3 1819.06  4276.5 1817.18
  4344.8 1816.22  4384.8 1814.20  4444.9 1815.06  4534.9 1812.59  4620.8 1812.23
  4691.4 1813.77  4794.2 1813.73  4816.0 1813.58  4860.9 1812.56  4902.6 1810.05
  4945.6 1809.76  4974.3 1806.99  4996.1 1806.94  4996.6 1806.44  5003.9 1806.94
  5108.5 1808.80  5435.8 1811.61  5551.3 1811.44  5716.9 1816.15  5835.0 1820.82
  5959.4 1824.15  5965.4 1825.73  5970.5 1824.40  5990.0 1826.84  6012.1 1827.43
#Mann=10,-1,0
  3917.0   0.094       0  4036.3   0.035       0  4276.5   0.063       0
  4620.8   0.035       0  4691.4   0.125       0  4794.2   0.035       0
  4816.0    0.07       0  4996.1    0.07       0  5003.9    0.07       0
  5835.0   0.035       0
Bank Sta=4996.1,5003.9
Exp/Cntr=0.3,0.1

Type RM Length L Ch R = 1,59018,547,547,547
BEGIN DESCRIPTION:
Cat Claw Creek 62.0
END DESCRIPTION:
XS GIS Cut Line= 3
      1572898.64      6817623.67      1573781.45      6817662.08
      1575055.03      6817716.85
#Sta/Elev= 30
  3441.7 1821.02  3498.1 1819.06  3518.1 1820.44  3568.4 1819.05  3806.4 1817.22
  3890.0 1816.14  3918.5 1814.25  4155.4 1812.31  4224.9 1813.94  4409.0 1812.88
  4459.0 1811.33  4521.8 1812.41  4581.8 1810.89  4609.2 1806.38  4635.4 1805.99
  4699.2 1806.40  4719.3 1809.17  4749.3 1807.02  4854.5 1807.53  4932.7 1806.35
  4996.0 1805.29  4996.5 1804.79  5004.1 1805.29  5017.1 1805.38  5099.6 1806.06
  5189.7 1815.05  5317.8 1820.43  5395.3 1823.75  5550.0 1832.56  5600.1 1833.96
#Mann=14,-1,0
  3441.7   0.094       0  3568.4   0.035       0  3806.4   0.063       0
  4155.4   0.035       0  4224.9   0.125       0  4521.8    0.07       0
  4635.4   0.035       0  4854.5    0.07       0  4932.7   0.035       0
  4996.0   0.035       0  5004.1   0.035       0  5017.1    0.07       0
  5317.8   0.035       0  5395.3    0.07       0
Bank Sta=4996,5004.1
Exp/Cntr=0.3,0.1

Type RM Length L Ch R = 1,58471,674,674,674
BEGIN DESCRIPTION:
Cat Claw Creek 61.0
END DESCRIPTION:
XS GIS Cut Line= 3
      1572983.42      6817735.02      1573969.91      6817961.84
      1574886.49      6818568.88
#Sta/Elev= 30
  3727.5 1819.04  3732.4 1818.99  3833.5 1817.94  3897.7 1817.94  3988.5 1815.36
  4026.2 1816.75  4273.0 1812.62  4700.2 1811.13  4818.4 1810.86  4881.6 1811.43
  4936.4 1811.51  4957.4 1810.15  4993.5 1804.52  4995.9 1802.15  4996.4 1801.65
  5004.1 1802.15  5008.6 1804.27  5071.7 1805.03  5093.7 1802.15  5101.9 1804.05
  5122.9 1805.14  5206.4 1805.56  5210.7 1805.61  5303.4 1806.07  5369.5 1808.25
  5395.7 1810.53  5438.7 1812.45  5555.3 1820.13  5725.1 1828.27  5839.1 1830.82
#Mann=14,-1,0
  3727.5   0.094       0  3732.4   0.035       0  3833.5   0.063       0
  4700.2   0.035       0  4818.4   0.063       0  4881.6   0.035       0
  4995.9   0.035       0  5004.1   0.035       0  5206.4    0.07       0
  5210.7   0.063       0  5395.7   0.035       0  5438.7    0.07       0
  5555.3   0.035       0  5725.1    0.07       0
Bank Sta=4995.9,5004.1
Exp/Cntr=0.3,0.1

Type RM Length L Ch R = 1,57797,576,576,576
BEGIN DESCRIPTION:
Cat Claw Creek 60.0
END DESCRIPTION:
XS GIS Cut Line= 3
      1573305.03      6818138.02      1574115.90      6818728.37
      1574504.97      6819087.97
#Sta/Elev= 30
  3997.0 1815.18  4146.5 1814.23  4190.5 1812.81  4267.2 1812.62  4512.7 1809.90
  4556.6 1808.58  4612.8 1808.42  4676.6 1807.49  4734.5 1807.28  4770.0 1806.04
  4790.9 1804.27  4799.4 1802.14  4826.4 1801.10  4931.9 1801.43  4995.9 1799.07
  4996.4 1798.57  5004.2 1799.07  5055.5 1799.21  5076.5 1800.60  5112.2 1801.60
  5126.4 1802.80  5133.8 1805.47  5148.0 1807.25  5189.9 1807.23  5225.6 1808.65
  5339.0 1809.57  5345.8 1808.26  5395.2 1809.34  5494.4 1813.35  5529.8 1815.71
#Mann=9,-1,0
  3997.0   0.063       0  4267.2   0.035       0  4556.6    0.07       0
  4612.8   0.035       0  4676.6    0.07       0  4931.9    0.16       0
  4995.9    0.07       0  5004.2    0.16       0  5076.5    0.07       0
Bank Sta=4995.9,5004.2
Exp/Cntr=0.3,0.1

Type RM Length L Ch R = 1,57221,204,204,204
BEGIN DESCRIPTION:
Cat Claw Creek 59.0
END DESCRIPTION:
XS GIS Cut Line= 3
      1573270.22      6818218.90      1574188.47      6819772.98
      1574457.81      6819963.33
#Sta/Elev= 30
  3850.0 1813.62  3918.6 1813.92  4049.7 1811.80  4396.5 1809.20  4517.4 1806.26
  4591.7 1805.92  4627.7 1805.59  4677.3 1805.06  4708.5 1801.32  4777.5 1801.01
  4948.5 1799.87  4995.9 1798.09  4996.4 1797.59  5004.2 1798.09  5012.8 1799.12
  5090.2 1799.72  5149.0 1800.25  5205.8 1800.62  5299.6 1801.52  5326.9 1803.51
  5385.4 1802.59  5416.7 1803.57  5438.1 1801.34  5535.9 1802.76  5722.0 1805.16
  5790.7 1807.52  5822.3 1809.15  5843.2 1813.63  5933.5 1816.17  5984.9 1817.32
#Mann=15,-1,0
  3850.0   0.063       0  4049.7   0.035       0  4396.5   0.094       0
  4591.7   0.035       0  4627.7   0.094       0  4777.5   0.035       0
  4995.9   0.035       0  5004.2   0.035       0  5090.2   0.063       0
  5149.0   0.035       0  5205.8   0.063       0  5535.9    0.07       0
  5722.0   0.035       0  5790.7    0.07       0  5933.5   0.094       0
Bank Sta=4995.9,5004.2
Exp/Cntr=0.3,0.1

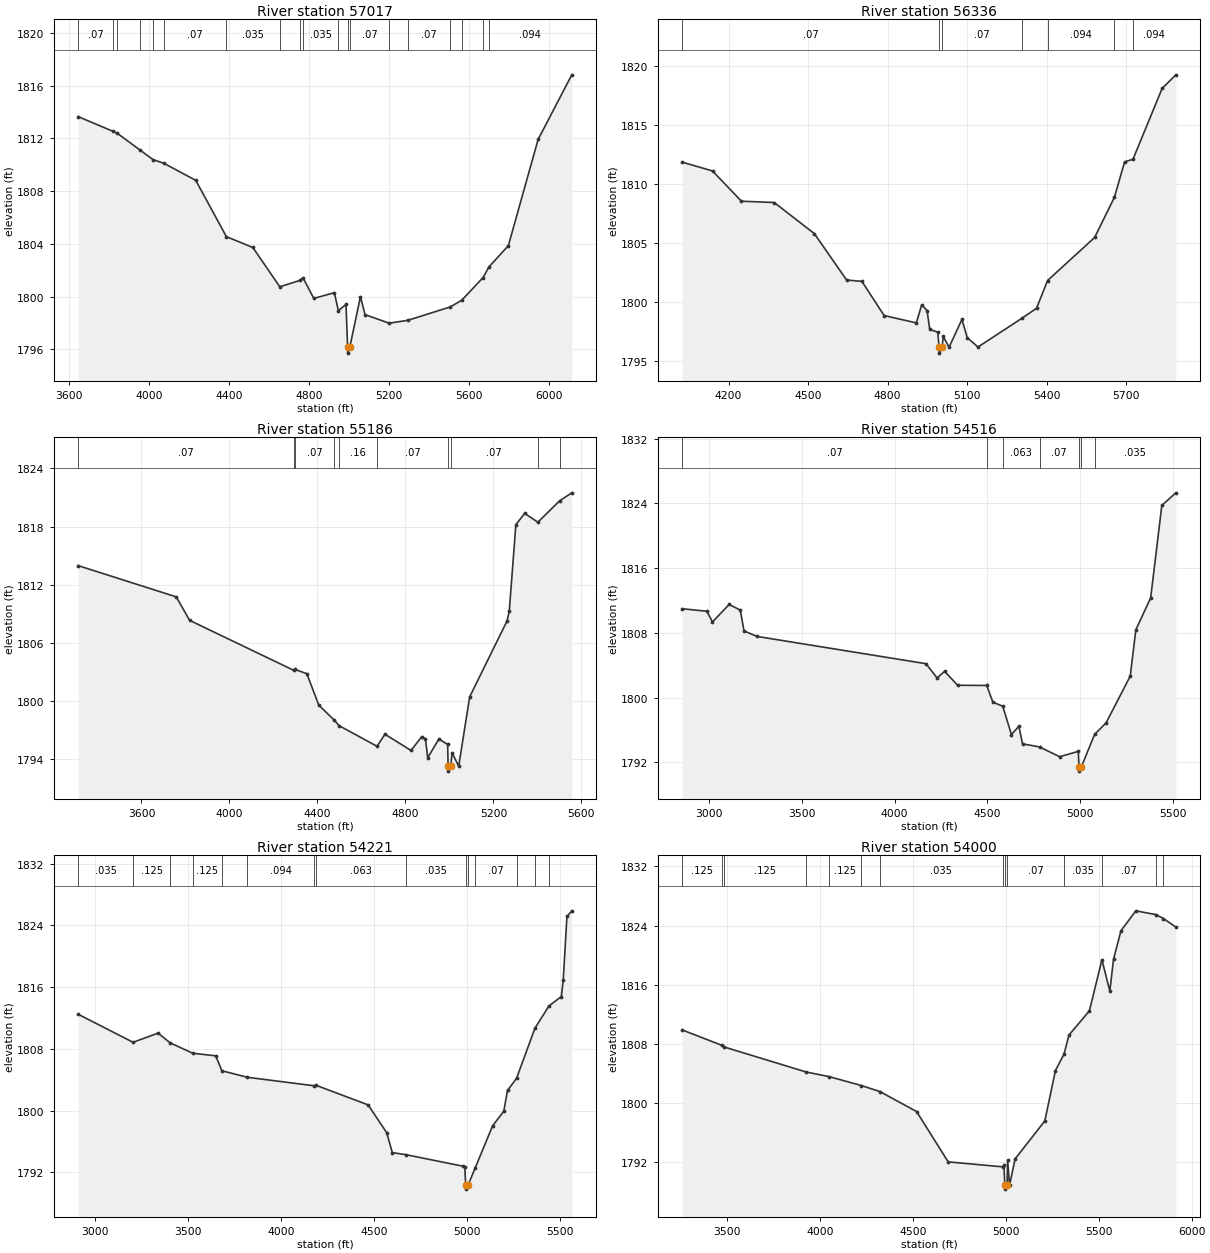
Type RM Length L Ch R = 1,57017,681,681,681
BEGIN DESCRIPTION:
Cat Claw Creek 58.0
END DESCRIPTION:
XS GIS Cut Line= 3
      1573067.45      6818217.97      1574126.31      6819978.04
      1574437.27      6820253.88
#Sta/Elev= 30
  3646.4 1813.64  3821.4 1812.52  3841.7 1812.38  3957.9 1811.08  4020.9 1810.38
  4074.1 1810.11  4234.5 1808.81  4387.8 1804.54  4520.1 1803.72  4655.0 1800.74
  4754.8 1801.22  4771.2 1801.42  4825.1 1799.86  4928.0 1800.29  4947.9 1798.93
  4986.3 1799.40  4994.2 1796.21  4994.7 1795.71  5005.9 1796.21  5058.5 1799.99
  5081.4 1798.63  5202.2 1797.98  5296.3 1798.20  5507.4 1799.21  5565.5 1799.72
  5672.1 1801.44  5700.8 1802.23  5798.6 1803.86  5947.5 1811.91  6116.1 1816.81
#Mann=19,-1,0
  3646.4    0.07       0  3821.4   0.063       0  3841.7   0.094       0
  3957.9    0.16       0  4020.9   0.094       0  4074.1    0.07       0
  4387.8   0.035       0  4655.0    0.07       0  4754.8   0.094       0
  4771.2   0.035       0  4947.9    0.07       0  4994.2    0.07       0
  5005.9    0.07       0  5202.2   0.063       0  5296.3    0.07       0
  5507.4   0.035       0  5565.5    0.07       0  5672.1   0.035       0
  5700.8   0.094       0
Bank Sta=4994.2,5005.9
Exp/Cntr=0.3,0.1

Type RM Length L Ch R = 1,56336,1150,1150,1150
BEGIN DESCRIPTION:
Cat Claw Creek 57.0
END DESCRIPTION:
XS GIS Cut Line= 3
      1572792.06      6819738.04      1573984.59      6819924.36
      1574460.27      6820375.66
#Sta/Elev= 30
  4024.9 1811.86  4139.2 1811.11  4248.4 1808.54  4372.0 1808.43  4523.8 1805.78
  4645.3 1801.84  4702.9 1801.73  4787.0 1798.82  4908.4 1798.20  4928.7 1799.74
  4948.9 1799.25  4959.0 1797.64  4989.4 1797.41  4994.1 1796.13  4994.6 1795.63
  5005.9 1796.13  5009.6 1797.06  5031.8 1796.13  5080.5 1798.49  5100.7 1796.94
  5141.2 1796.15  5306.7 1798.59  5362.0 1799.44  5403.7 1801.80  5581.3 1805.46
  5655.8 1808.87  5694.5 1811.89  5725.9 1812.10  5836.1 1818.13  5887.6 1819.28
#Mann=7,-1,0
  4024.9    0.07       0  4994.1    0.07       0  5005.9    0.07       0
  5306.7   0.035       0  5403.7   0.094       0  5655.8   0.035       0
  5725.9   0.094       0
Bank Sta=4994.1,5005.9
Exp/Cntr=0.3,0.1

Type RM Length L Ch R = 1,55186,670,670,670
BEGIN DESCRIPTION:
Cat Claw Creek 56.0
END DESCRIPTION:
XS GIS Cut Line= 4
      1572388.72      6820191.15      1573377.99      6820570.57
      1573926.22      6820450.01      1574549.28      6820440.39
#Sta/Elev= 30
  3312.5 1813.98  3758.3 1810.76  3818.8 1808.34  4292.8 1803.18  4296.7 1803.29
  4351.8 1802.84  4406.0 1799.60  4475.9 1798.06  4498.3 1797.48  4671.2 1795.35
  4706.9 1796.60  4825.5 1794.92  4874.3 1796.35  4891.2 1796.11  4901.4 1794.17
  4952.1 1796.10  4992.1 1795.54  4994.1 1793.29  4994.6 1792.79  5006.0 1793.29
  5012.2 1794.69  5042.2 1793.29  5092.2 1800.45  5262.2 1808.28  5272.2 1809.30
  5302.2 1818.21  5342.2 1819.37  5402.2 1818.46  5501.2 1820.67  5556.5 1821.49
#Mann=10,-1,0
  3312.5    0.07       0  4292.8   0.035       0  4296.7    0.07       0
  4475.9   0.035       0  4498.3    0.16       0  4671.2    0.07       0
  4994.1    0.07       0  5006.0    0.07       0  5402.2   0.035       0
  5501.2   0.094       0
Bank Sta=4994.1,5006
Exp/Cntr=0.3,0.1

Type RM Length L Ch R = 1,54516,295,295,295
BEGIN DESCRIPTION:
Cat Claw Creek 55.4
END DESCRIPTION:
XS GIS Cut Line= 3
      1571962.25      6820886.80      1573974.48      6820940.56
      1574620.43      6820939.83
#Sta/Elev= 30
  2856.4 1810.99  2989.2 1810.68  3019.2 1809.36  3109.2 1811.52  3169.3 1810.82
  3189.3 1808.25  3259.3 1807.57  4169.6 1804.20  4229.6 1802.44  4269.7 1803.27
  4339.7 1801.54  4497.0 1801.51  4529.7 1799.45  4583.1 1798.95  4629.8 1795.44
  4669.8 1796.48  4689.8 1794.30  4781.0 1793.92  4889.9 1792.71  4989.9 1793.37
  4994.0 1791.43  4994.5 1790.93  5006.0 1791.43  5077.9 1795.47  5139.9 1796.90
  5269.9 1802.67  5299.9 1808.38  5379.9 1812.34  5439.9 1823.75  5515.3 1825.31
#Mann=7,-1,0
  2856.4    0.07       0  4497.0   0.035       0  4583.1   0.063       0
  4781.0    0.07       0  4994.0    0.07       0  5006.0    0.07       0
  5077.9   0.035       0
Bank Sta=4994,5006
Exp/Cntr=0.3,0.1

Type RM Length L Ch R = 1,54221,221,221,221
BEGIN DESCRIPTION:
Cat Claw Creek 55.2
END DESCRIPTION:
XS GIS Cut Line= 3
      1572015.38      6821277.65      1574026.00      6821203.30
      1574671.21      6821202.57
#Sta/Elev= 30
  2907.8 1812.48  3202.9 1808.85  3337.7 1810.04  3402.6 1808.78  3524.5 1807.43
  3647.9 1807.10  3681.6 1805.16  3817.9 1804.32  4177.3 1803.22  4186.0 1803.30
  4468.5 1800.74  4568.6 1797.14  4598.6 1794.56  4673.1 1794.29  4978.8 1792.80
  4988.8 1792.66  4993.9 1790.33  4994.4 1789.83  5006.1 1790.33  5044.7 1792.57
  5138.8 1798.04  5198.8 1799.91  5218.8 1802.61  5267.5 1804.18  5366.5 1810.67
  5442.0 1813.56  5508.8 1814.78  5518.8 1816.94  5538.8 1825.15  5565.0 1825.88
#Mann=15,-1,0
  2907.8   0.035       0  3202.9   0.125       0  3402.6   0.094       0
  3524.5   0.125       0  3681.6   0.063       0  3817.9   0.094       0
  4177.3   0.035       0  4186.0   0.063       0  4673.1   0.035       0
  4993.9   0.035       0  5006.1   0.035       0  5044.7    0.07       0
  5267.5   0.035       0  5366.5   0.094       0  5442.0   0.125       0
Bank Sta=4993.9,5006.1
Exp/Cntr=0.3,0.1

Type RM Length L Ch R = 1,54000,470,470,470
BEGIN DESCRIPTION:
Cat Claw Creek 55.0
END DESCRIPTION:
XS GIS Cut Line= 3
      1572313.81      6821473.30      1574324.36      6821398.98
      1574970.34      6821398.25
#Sta/Elev= 30
  3256.9 1809.90  3472.7 1807.80  3482.4 1807.60  3924.5 1804.22  4048.7 1803.59
  4222.0 1802.39  4321.2 1801.58  4518.9 1798.88  4689.1 1792.08  4983.9 1791.41
  4989.3 1791.70  4993.9 1788.90  4994.4 1788.40  5006.1 1788.90  5009.3 1792.30
  5019.3 1788.90  5049.3 1792.48  5209.4 1797.61  5266.6 1804.42  5312.6 1806.62
  5339.5 1809.21  5449.5 1812.48  5517.0 1819.38  5559.5 1815.14  5579.5 1819.47
  5619.5 1823.30  5699.5 1825.99  5807.6 1825.48  5848.4 1824.95  5914.8 1823.80
#Mann=14,-1,0
  3256.9   0.125       0  3472.7   0.094       0  3482.4   0.125       0
  3924.5   0.094       0  4048.7   0.125       0  4222.0   0.063       0
  4321.2   0.035       0  4983.9    0.07       0  4993.9    0.07       0
  5006.1    0.07       0  5312.6   0.035       0  5517.0    0.07       0
  5807.6   0.035       0  5848.4   0.125       0
Bank Sta=4993.9,5006.1
Exp/Cntr=0.3,0.1