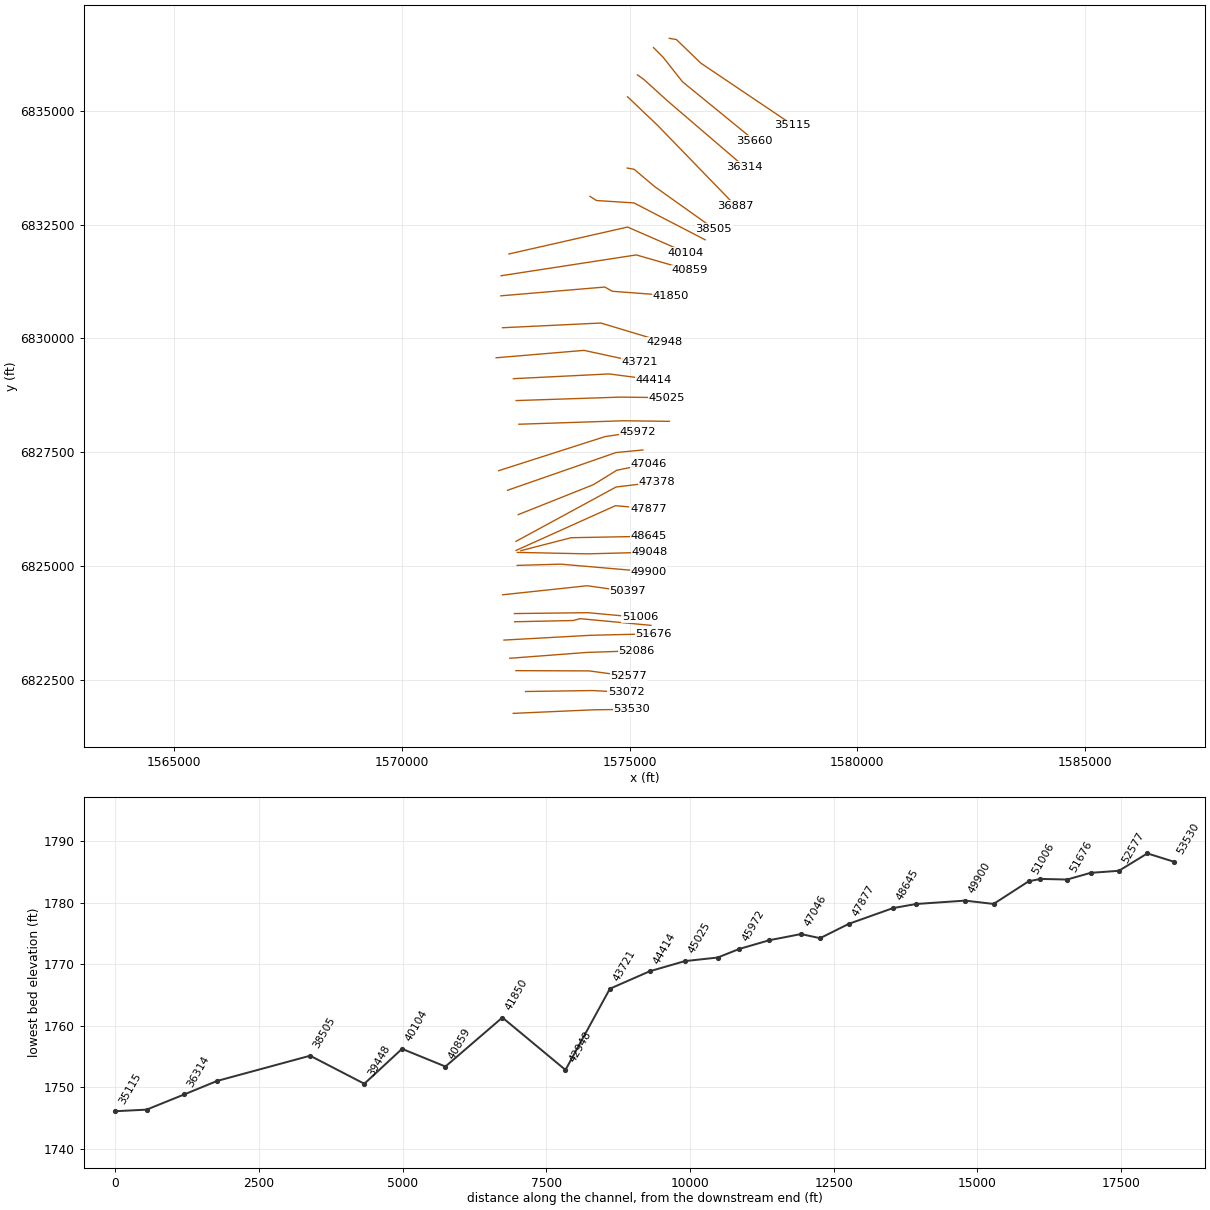
HEC-RAS study Cat Claw Creek.prj: Cat Claw Creek Base Level Engineering

--- Cat Claw Creek.g01 (geometry) --- (continued)

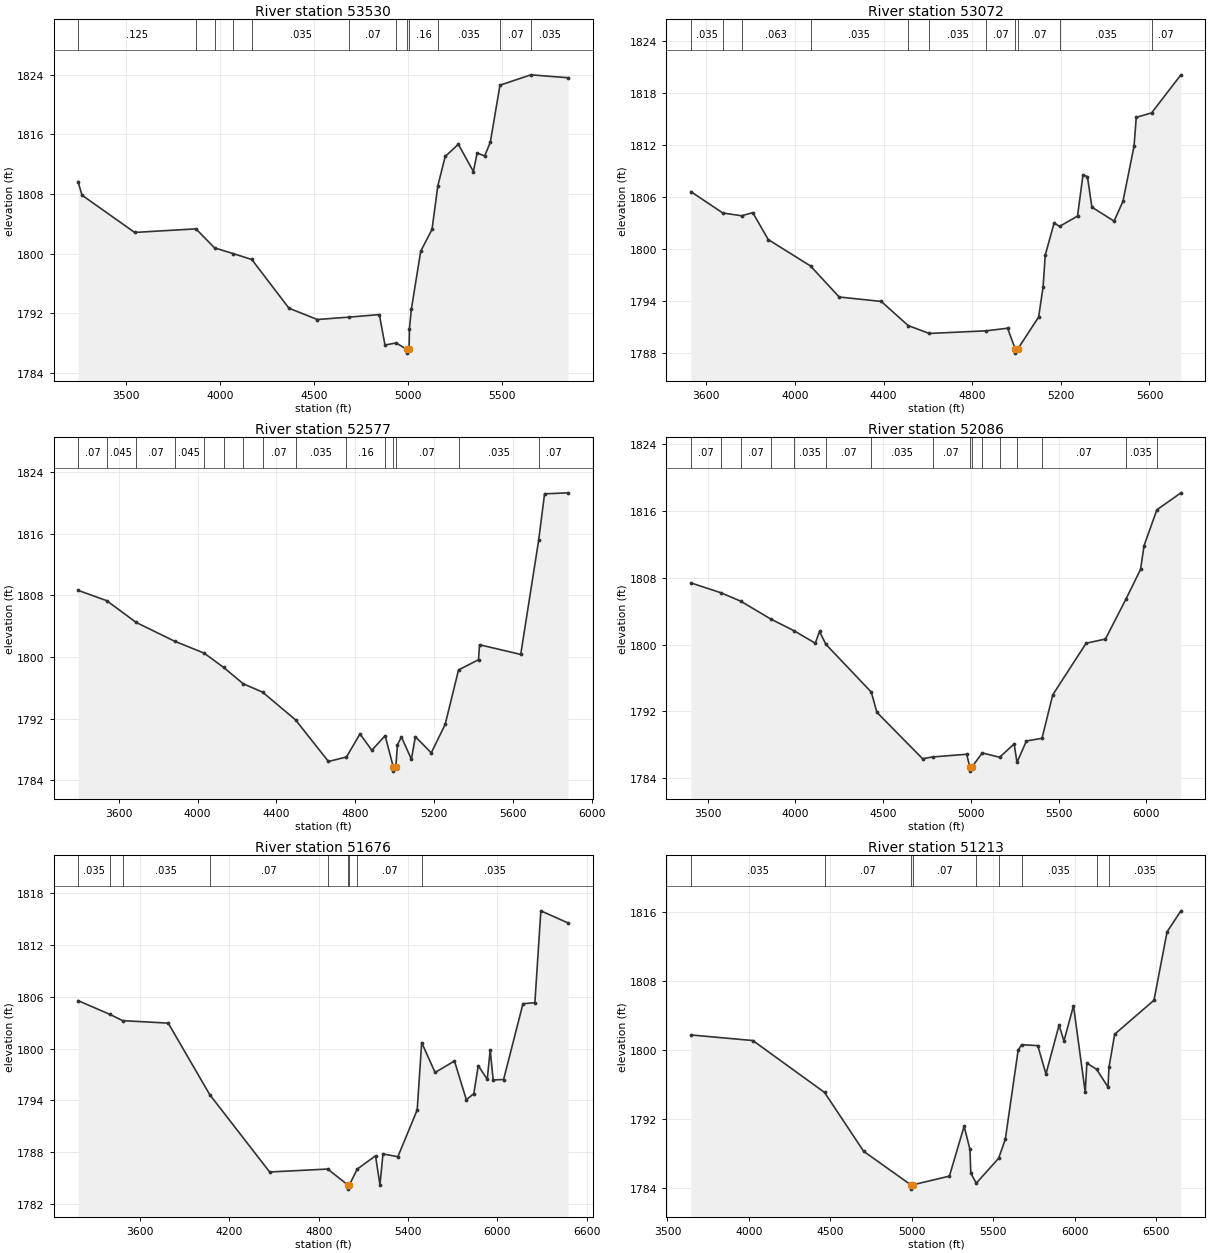
Type RM Length L Ch R = 1,53530,458,458,458
BEGIN DESCRIPTION:
Cat Claw Creek 54.0
END DESCRIPTION:
XS GIS Cut Line= 3
      1572444.10      6821756.43      1574196.96      6821834.68
      1575048.59      6821845.74
#Sta/Elev= 30
  3245.4 1809.67  3266.3 1807.86  3546.6 1802.86  3872.5 1803.34  3971.4 1800.79
  4070.4 1800.02  4169.4 1799.23  4367.4 1792.69  4518.2 1791.18  4687.4 1791.50
  4847.9 1791.84  4877.9 1787.75  4937.3 1788.04  4993.9 1787.17  4994.4 1786.67
  5006.1 1787.17  5008.0 1789.95  5018.0 1792.54  5068.0 1800.34  5128.1 1803.27
  5159.0 1809.11  5198.1 1813.05  5268.1 1814.68  5348.1 1811.03  5368.1 1813.52
  5408.1 1813.12  5438.1 1814.95  5489.5 1822.61  5653.8 1824.00  5851.7 1823.61
#Mann=12,-1,0
  3245.4   0.125       0  3872.5   0.094       0  3971.4   0.063       0
  4070.4   0.094       0  4169.4   0.035       0  4687.4    0.07       0
  4937.3    0.16       0  4993.9    0.07       0  5006.1    0.16       0
  5159.0   0.035       0  5489.5    0.07       0  5653.8   0.035       0
Bank Sta=4993.9,5006.1
Exp/Cntr=0.3,0.1

Type RM Length L Ch R = 1,53072,495,495,495
BEGIN DESCRIPTION:
Cat Claw Creek 53.0
END DESCRIPTION:
XS GIS Cut Line= 3
      1572715.70      6822237.14      1574185.35      6822258.14
      1574926.23      6822217.36
#Sta/Elev= 30
  3530.2 1806.63  3674.3 1804.17  3759.0 1803.85  3809.5 1804.21  3879.5 1801.10
  4070.2 1798.06  4199.6 1794.48  4389.6 1793.97  4510.9 1791.19  4605.8 1790.28
  4861.8 1790.58  4959.6 1790.88  4993.9 1788.51  4994.4 1788.01  5006.2 1788.51
  5099.8 1792.17  5119.8 1795.62  5129.8 1799.33  5169.9 1803.03  5194.0 1802.62
  5275.3 1803.81  5300.1 1808.58  5320.1 1808.36  5340.2 1804.84  5440.3 1803.23
  5480.4 1805.51  5530.4 1811.87  5540.5 1815.20  5609.7 1815.71  5742.0 1820.10
#Mann=11,-1,0
  3530.2   0.035       0  3674.3   0.094       0  3759.0   0.063       0
  4070.2   0.035       0  4510.9    0.07       0  4605.8   0.035       0
  4861.8    0.07       0  4993.9    0.07       0  5006.2    0.07       0
  5194.0   0.035       0  5609.7    0.07       0
Bank Sta=4993.9,5006.2
Exp/Cntr=0.3,0.1

Type RM Length L Ch R = 1,52577,491,491,491
BEGIN DESCRIPTION:
Cat Claw Creek 52.0
END DESCRIPTION:
XS GIS Cut Line= 3
      1572503.89      6822695.28      1574110.38      6822690.18
      1574983.22      6822572.78
#Sta/Elev= 30
  3393.5 1808.64  3538.7 1807.30  3688.8 1804.47  3883.4 1802.04  4033.7 1800.49
  4132.7 1798.63  4231.7 1796.52  4330.7 1795.42  4497.5 1791.83  4664.6 1786.43
  4756.0 1787.02  4824.6 1790.01  4884.6 1787.89  4952.2 1789.78  4993.9 1785.68
  4994.4 1785.18  5006.2 1785.68  5014.8 1788.61  5034.9 1789.61  5085.4 1786.73
  5105.6 1789.65  5186.3 1787.55  5256.9 1791.24  5324.7 1798.31  5426.2 1799.64
  5431.2 1801.58  5640.3 1800.32  5731.4 1815.13  5761.4 1821.16  5880.7 1821.29
#Mann=15,-1,0
  3393.5    0.07       0  3538.7   0.045       0  3688.8    0.07       0
  3883.4   0.045       0  4033.7   0.035       0  4132.7    0.07       0
  4231.7   0.035       0  4330.7    0.07       0  4497.5   0.035       0
  4756.0    0.16       0  4952.2    0.07       0  4993.9    0.07       0
  5006.2    0.07       0  5324.7   0.035       0  5731.4    0.07       0
Bank Sta=4993.9,5006.2
Exp/Cntr=0.3,0.1

Type RM Length L Ch R = 1,52086,410,410,410
BEGIN DESCRIPTION:
Cat Claw Creek 51.0
END DESCRIPTION:
XS GIS Cut Line= 3
      1572368.27      6822967.42      1574061.10      6823096.26
      1575154.87      6823132.81
#Sta/Elev= 30
  3404.5 1807.38  3574.0 1806.21  3688.7 1805.19  3859.1 1803.06  3990.0 1801.68
  4113.3 1800.16  4137.6 1801.57  4173.2 1800.04  4432.5 1794.31  4464.3 1791.89
  4725.0 1786.33  4782.7 1786.55  4975.8 1786.87  4993.8 1785.35  4994.3 1784.85
  5006.2 1785.35  5064.7 1787.03  5163.7 1786.51  5246.2 1788.11  5262.7 1785.90
  5316.2 1788.46  5405.1 1788.78  5466.3 1793.98  5656.4 1800.16  5766.5 1800.66
  5882.5 1805.40  5966.6 1809.00  5986.6 1811.84  6059.4 1816.12  6196.6 1818.16
#Mann=16,-1,0
  3404.5    0.07       0  3574.0   0.045       0  3688.7    0.07       0
  3859.1   0.045       0  3990.0   0.035       0  4173.2    0.07       0
  4432.5   0.035       0  4782.7    0.07       0  4993.8    0.07       0
  5006.2    0.07       0  5064.7   0.035       0  5163.7    0.07       0
  5262.7    0.16       0  5405.1    0.07       0  5882.5   0.035       0
  6059.4    0.07       0
Bank Sta=4993.8,5006.2
Exp/Cntr=0.3,0.1

Type RM Length L Ch R = 1,51676,463,463,463
BEGIN DESCRIPTION:
Cat Claw Creek 50.0
END DESCRIPTION:
XS GIS Cut Line= 3
      1572240.29      6823367.59      1574138.16      6823472.58
      1575527.79      6823505.54
#Sta/Elev= 30
  3183.5 1805.53  3396.2 1803.95  3483.0 1803.22  3789.1 1802.93  4068.4 1794.66
  4470.2 1785.74  4860.2 1786.08  4993.8 1784.26  4994.3 1783.76  5006.2 1784.26
  5058.2 1786.07  5181.1 1787.61  5211.1 1784.26  5231.2 1787.83  5331.2 1787.50
  5461.2 1792.91  5491.1 1800.68  5581.3 1797.23  5711.3 1798.56  5791.3 1794.08
  5841.3 1794.79  5871.3 1798.02  5931.4 1796.44  5951.4 1799.83  5971.4 1796.37
  6041.4 1796.42  6171.4 1805.17  6251.4 1805.29  6291.5 1815.90  6474.3 1814.50
#Mann=9,-1,0
  3183.5   0.035       0  3396.2    0.07       0  3483.0   0.035       0
  4068.4    0.07       0  4860.2    0.16       0  4993.8    0.07       0
  5006.2    0.16       0  5058.2    0.07       0  5491.1   0.035       0
Bank Sta=4993.8,5006.2
Exp/Cntr=0.3,0.1

Type RM Length L Ch R = 1,51213,207,207,207
BEGIN DESCRIPTION:
Cat Claw Creek 49.0
END DESCRIPTION:
XS GIS Cut Line= 4
      1572474.73      6823770.45      1573761.59      6823797.47
      1573913.09      6823838.34      1575469.60      6823691.31
#Sta/Elev= 30
  3643.9 1801.76  4024.3 1801.11  4464.0 1795.09  4704.4 1788.25  4993.6 1784.36
  4994.1 1783.86  5006.4 1784.36  5230.5 1785.37  5320.9 1791.16  5356.7 1788.47
  5361.7 1785.71  5395.5 1784.55  5532.5 1787.44  5573.6 1789.64  5652.4 1799.98
  5673.5 1800.63  5772.9 1800.52  5823.1 1797.23  5903.5 1802.90  5933.6 1801.06
  5992.1 1805.15  6064.2 1795.11  6074.2 1798.49  6134.0 1797.77  6204.0 1795.71
  6209.9 1798.01  6245.0 1801.85  6486.1 1805.79  6566.4 1813.73  6651.4 1816.17
#Mann=9,-1,0
  3643.9   0.035       0  4464.0    0.07       0  4993.6    0.07       0
  5006.4    0.07       0  5395.5    0.16       0  5532.5    0.07       0
  5673.5   0.035       0  6134.0    0.07       0  6209.9   0.035       0
Bank Sta=4993.6,5006.4
Exp/Cntr=0.3,0.1

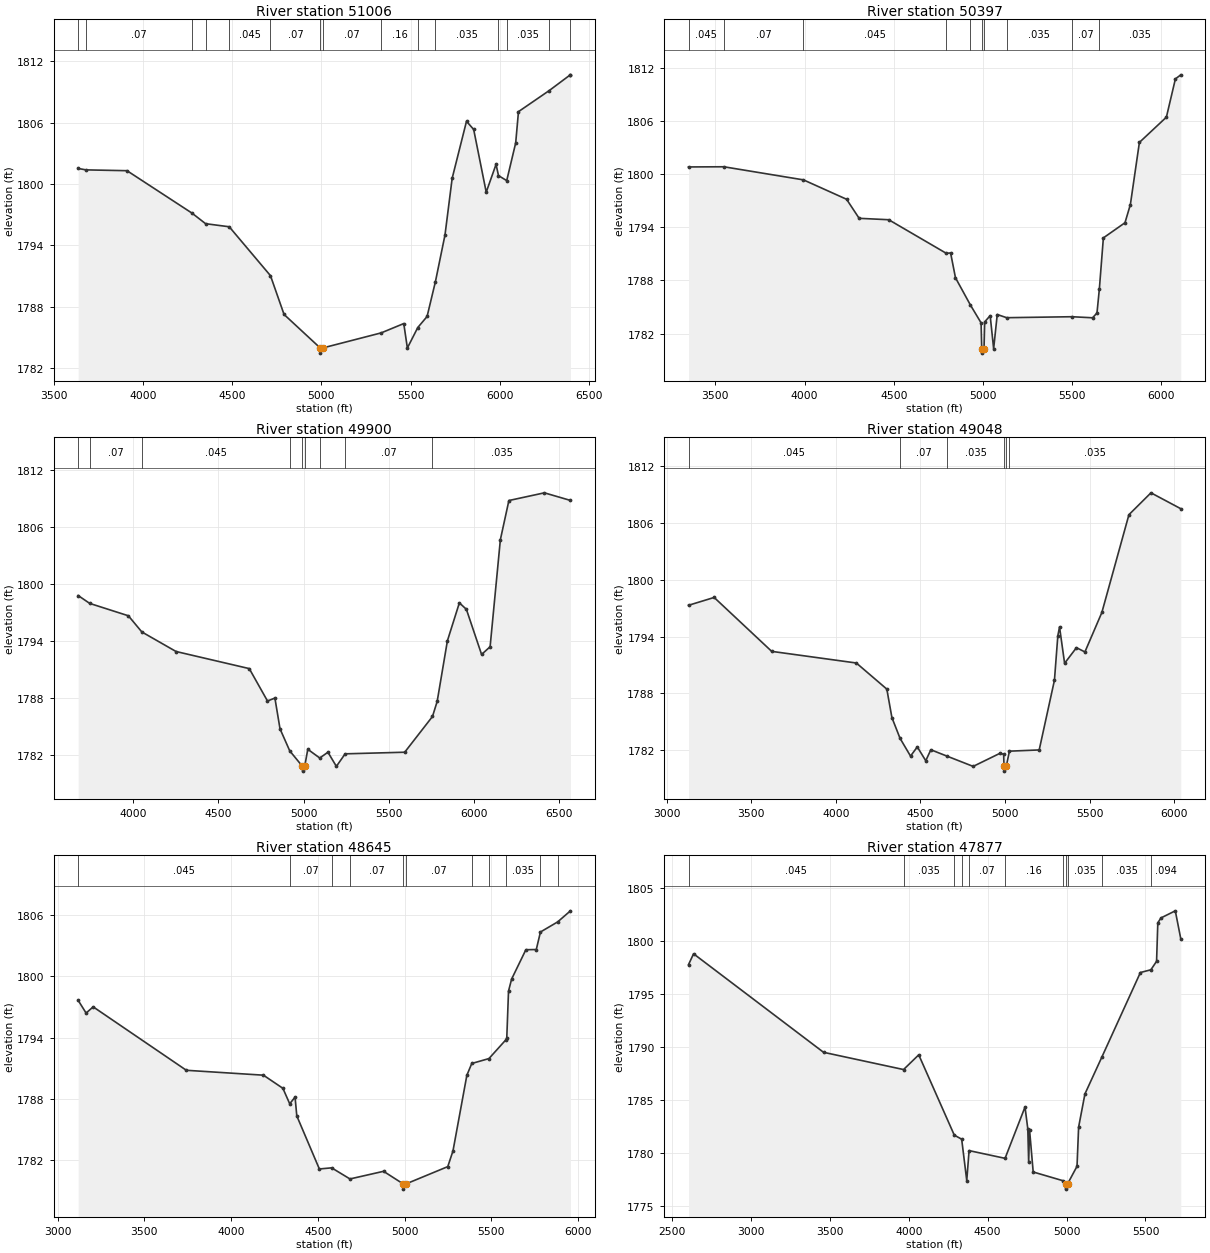
Type RM Length L Ch R = 1,51006,609,609,609
BEGIN DESCRIPTION:
Cat Claw Creek 48.0
END DESCRIPTION:
XS GIS Cut Line= 3
      1572471.28      6823950.44      1574080.34      6823969.78
      1575225.07      6823864.98
#Sta/Elev= 30
  3636.9 1801.52  3680.5 1801.38  3910.6 1801.30  4274.3 1797.16  4351.1 1796.12
  4483.5 1795.82  4714.6 1791.04  4790.7 1787.25  4993.6 1783.97  4994.1 1783.47
  5006.4 1783.97  5335.3 1785.45  5461.6 1786.36  5481.7 1783.97  5540.0 1785.97
  5592.2 1787.05  5639.0 1790.46  5692.6 1795.02  5732.8 1800.56  5813.1 1806.13
  5853.3 1805.33  5923.6 1799.20  5978.7 1801.92  5992.4 1800.82  6038.5 1800.33
  6088.8 1804.02  6104.3 1807.07  6275.7 1809.12  6394.8 1810.67  6395.6 1810.67
#Mann=15,-1,0
  3636.9   0.045       0  3680.5    0.07       0  4274.3   0.045       0
  4351.1    0.07       0  4483.5   0.045       0  4714.6    0.07       0
  4993.6    0.07       0  5006.4    0.07       0  5335.3    0.16       0
  5540.0    0.07       0  5639.0   0.035       0  5992.4    0.07       0
  6038.5   0.035       0  6275.7    0.07       0  6394.8   0.035       0
Bank Sta=4993.6,5006.4
Exp/Cntr=0.3,0.1

Type RM Length L Ch R = 1,50397,497,497,497
BEGIN DESCRIPTION:
Cat Claw Creek 47.0
END DESCRIPTION:
XS GIS Cut Line= 3
      1572213.65      6824363.64      1574067.29      6824561.80
      1574955.00      6824438.00
#Sta/Elev= 30
  3349.4 1800.81  3547.3 1800.83  3994.0 1799.35  4235.8 1797.16  4306.2 1795.01
  4472.2 1794.85  4794.8 1791.06  4819.1 1791.10  4846.4 1788.30  4930.2 1785.22
  4990.0 1783.21  4993.6 1780.29  4994.1 1779.79  5006.5 1780.29  5010.2 1783.32
  5041.0 1784.02  5060.4 1780.29  5080.6 1784.15  5133.6 1783.79  5499.5 1783.90
  5615.2 1783.78  5639.9 1784.32  5653.2 1787.03  5675.7 1792.80  5796.9 1794.51
  5827.2 1796.57  5877.7 1803.58  6029.1 1806.43  6079.6 1810.75  6109.9 1811.21
#Mann=10,-1,0
  3349.4   0.045       0  3547.3    0.07       0  3994.0   0.045       0
  4794.8   0.035       0  4930.2    0.07       0  4993.6    0.07       0
  5006.5    0.07       0  5133.6   0.035       0  5499.5    0.07       0
  5653.2   0.035       0
Bank Sta=4993.6,5006.5
Exp/Cntr=0.3,0.1

Type RM Length L Ch R = 1,49900,852,852,852
BEGIN DESCRIPTION:
Cat Claw Creek 46.2
END DESCRIPTION:
XS GIS Cut Line= 3
      1572530.06      6825009.06      1573489.07      6825036.33
      1575415.32      6824870.08
#Sta/Elev= 30
  3675.4 1798.81  3743.6 1797.98  3970.5 1796.68  4049.5 1794.98  4250.6 1792.92
  4680.9 1791.12  4788.0 1787.71  4831.5 1788.02  4861.6 1784.78  4918.8 1782.46
  4993.6 1780.83  4994.1 1780.33  5006.5 1780.83  5024.8 1782.63  5095.1 1781.71
  5143.1 1782.32  5192.8 1780.83  5244.2 1782.15  5594.3 1782.32  5757.5 1786.08
  5785.0 1787.66  5845.2 1794.05  5915.5 1798.04  5956.7 1797.36  6046.0 1792.61
  6096.1 1793.42  6156.4 1804.69  6206.5 1808.81  6415.1 1809.62  6568.2 1808.82
#Mann=9,-1,0
  3675.4   0.045       0  3743.6    0.07       0  4049.5   0.045       0
  4918.8    0.07       0  4993.6    0.07       0  5006.5    0.07       0
  5095.1   0.035       0  5244.2    0.07       0  5757.5   0.035       0
Bank Sta=4993.6,5006.5
Exp/Cntr=0.3,0.1

Type RM Length L Ch R = 1,49048,403,403,403
BEGIN DESCRIPTION:
Cat Claw Creek 46.0
END DESCRIPTION:
XS GIS Cut Line= 3
      1572533.57      6825294.71      1574075.82      6825262.93
      1575441.28      6825298.24
#Sta/Elev= 30
  3129.4 1797.31  3280.9 1798.14  3620.9 1792.44  4121.0 1791.21  4301.1 1788.45
  4331.1 1785.44  4379.1 1783.25  4441.1 1781.37  4481.1 1782.34  4531.1 1780.88
  4561.1 1782.04  4657.3 1781.36  4811.2 1780.28  4971.3 1781.68  4991.3 1781.55
  4993.5 1780.28  4994.0 1779.78  5006.6 1780.28  5025.4 1781.89  5201.3 1782.02
  5291.4 1789.39  5311.4 1794.09  5321.4 1795.02  5351.4 1791.18  5421.4 1792.83
  5471.4 1792.38  5571.5 1796.55  5731.5 1806.89  5861.6 1809.20  6037.9 1807.52
#Mann=6,-1,0
  3129.4   0.045       0  4379.1    0.07       0  4657.3   0.035       0
  4993.5   0.035       0  5006.6   0.035       0  5025.4   0.035       0
Bank Sta=4993.5,5006.6
Exp/Cntr=0.3,0.1

Type RM Length L Ch R = 1,48645,768,768,768
BEGIN DESCRIPTION:
Cat Claw Creek 45.0
END DESCRIPTION:
XS GIS Cut Line= 3
      1572611.16      6825332.71      1573716.52      6825617.91
      1575411.87      6825649.20
#Sta/Elev= 30
  3119.0 1797.65  3164.8 1796.40  3205.6 1797.01  3742.6 1790.78  4186.7 1790.30
  4299.0 1789.01  4338.3 1787.49  4369.1 1788.15  4379.1 1786.30  4509.1 1781.09
  4580.0 1781.20  4685.5 1780.11  4879.1 1780.86  4993.5 1779.61  4994.0 1779.11
  5006.6 1779.61  5249.2 1781.32  5279.2 1782.86  5359.2 1790.29  5387.5 1791.45
  5486.5 1791.93  5585.4 1793.80  5589.3 1793.98  5599.3 1798.56  5617.2 1799.74
  5699.3 1802.62  5759.3 1802.64  5783.3 1804.36  5882.3 1805.35  5956.2 1806.44
#Mann=11,-1,0
  3119.0   0.045       0  4338.3    0.07       0  4580.0   0.035       0
  4685.5    0.07       0  4993.5    0.07       0  5006.6    0.07       0
  5387.5   0.035       0  5486.5    0.07       0  5585.4   0.035       0
  5783.3   0.125       0  5882.3   0.035       0
Bank Sta=4993.5,5006.6
Exp/Cntr=0.3,0.1

Type RM Length L Ch R = 1,47877,499,499,499
BEGIN DESCRIPTION:
Cat Claw Creek 44.0
END DESCRIPTION:
XS GIS Cut Line= 3
      1572504.97      6825337.99      1574688.81      6826321.53
      1575410.05      6826259.62
#Sta/Elev= 30
  2604.9 1797.76  2636.9 1798.79  3460.4 1789.48  3967.3 1787.85  4063.6 1789.24
  4288.9 1781.65  4335.6 1781.27  4367.8 1777.36  4382.5 1780.19  4610.5 1779.46
  4736.9 1784.31  4754.5 1782.25  4760.0 1779.09  4765.5 1782.18  4788.7 1778.17
  4976.2 1777.35  4993.4 1777.05  4993.9 1776.55  5006.7 1777.05  5066.4 1778.71
  5076.5 1782.41  5116.6 1785.55  5225.0 1789.07  5467.9 1797.02  5534.5 1797.28
  5570.4 1798.08  5578.3 1801.72  5598.4 1802.18  5689.0 1802.85  5723.9 1800.20
#Mann=11,-1,0
  2604.9   0.045       0  3967.3   0.035       0  4288.9    0.07       0
  4335.6   0.035       0  4382.5    0.07       0  4610.5    0.16       0
  4976.2   0.035       0  4993.4   0.035       0  5006.7   0.035       0
  5225.0   0.035       0  5534.5   0.094       0
Bank Sta=4993.4,5006.7
Exp/Cntr=0.3,0.1

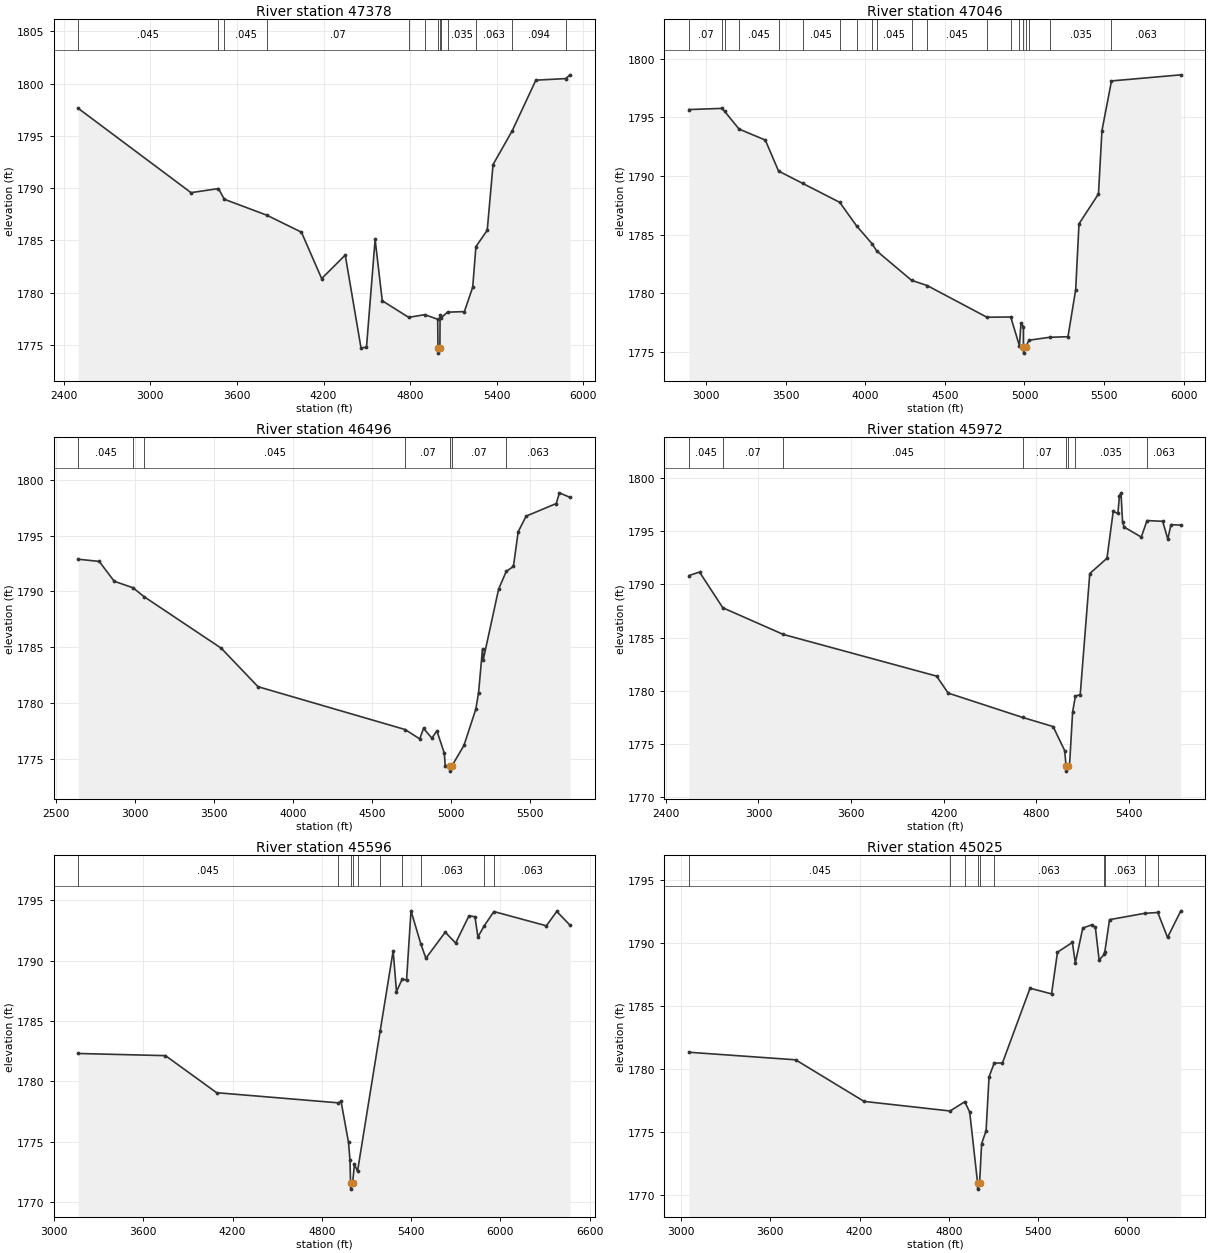
Type RM Length L Ch R = 1,47378,332,332,332
BEGIN DESCRIPTION:
Cat Claw Creek 43.0
END DESCRIPTION:
XS GIS Cut Line= 3
      1572505.02      6825538.01      1574702.51      6826731.98
      1575604.57      6826841.62
#Sta/Elev= 30
  2499.1 1797.64  3281.6 1789.57  3471.9 1789.96  3512.3 1788.94  3807.6 1787.41
  4046.9 1785.79  4187.2 1781.35  4350.6 1783.60  4459.9 1774.72  4497.9 1774.78
  4557.8 1785.09  4607.2 1779.23  4790.6 1777.64  4901.5 1777.90  4991.5 1777.46
  4993.4 1774.72  4993.9 1774.22  5006.7 1774.72  5008.0 1777.88  5016.2 1777.61
  5059.8 1778.14  5176.5 1778.19  5234.2 1780.53  5256.5 1784.41  5334.9 1785.97
  5375.2 1792.26  5508.1 1795.49  5672.0 1800.33  5878.9 1800.48  5908.7 1800.84
#Mann=13,-1,0
  2499.1   0.045       0  3471.9    0.07       0  3512.3   0.045       0
  3807.6    0.07       0  4790.6    0.16       0  4901.5   0.035       0
  4993.4   0.035       0  5006.7   0.035       0  5016.2    0.16       0
  5059.8   0.035       0  5256.5   0.063       0  5508.1   0.094       0
  5878.9   0.063       0
Bank Sta=4993.4,5006.7
Exp/Cntr=0.3,0.1

Type RM Length L Ch R = 1,47046,550,550,550
BEGIN DESCRIPTION:
Cat Claw Creek 42.0
END DESCRIPTION:
XS GIS Cut Line= 4
      1572554.71      6826125.52      1574203.47      6826782.94
      1574715.17      6827099.13      1575410.55      6827246.40
#Sta/Elev= 30
  2893.9 1795.65  3100.1 1795.75  3118.5 1795.49  3208.2 1793.99  3373.2 1793.05
  3456.2 1790.41  3607.5 1789.36  3840.5 1787.74  3945.9 1785.74  4043.4 1784.21
  4072.3 1783.60  4291.0 1781.10  4389.3 1780.65  4764.1 1777.95  4913.6 1777.97
  4968.1 1775.52  4977.8 1777.44  4993.2 1777.15  4993.3 1775.39  4993.8 1774.89
  5006.7 1775.39  5028.0 1775.99  5157.7 1776.24  5272.9 1776.29  5321.3 1780.30
  5342.1 1785.91  5464.4 1788.46  5486.1 1793.85  5546.0 1798.09  5981.2 1798.61
#Mann=20,-1,0
  2893.9    0.07       0  3100.1   0.045       0  3118.5    0.07       0
  3208.2   0.045       0  3456.2    0.07       0  3607.5   0.045       0
  3840.5    0.07       0  3945.9   0.045       0  4043.4    0.07       0
  4072.3   0.045       0  4291.0    0.07       0  4389.3   0.045       0
  4764.1    0.07       0  4913.6   0.035       0  4968.1    0.07       0
  4993.3    0.07       0  5006.7    0.07       0  5028.0   0.035       0
  5157.7   0.035       0  5546.0   0.063       0
Bank Sta=4993.3,5006.7
Exp/Cntr=0.3,0.1

Type RM Length L Ch R = 1,46496,524,524,524
BEGIN DESCRIPTION:
Cat Claw Creek 41.0
END DESCRIPTION:
XS GIS Cut Line= 3
      1572318.92      6826660.85      1574697.87      6827488.91
      1575291.74      6827546.44
#Sta/Elev= 30
  2638.0 1792.89  2771.5 1792.69  2866.8 1790.91  2985.2 1790.33  3057.8 1789.51
  3544.5 1784.91  3777.4 1781.46  4708.8 1777.62  4801.8 1776.78  4825.7 1777.72
  4878.6 1776.85  4910.4 1777.50  4957.2 1775.51  4963.3 1774.39  4993.3 1774.39
  4993.8 1773.89  5006.8 1774.39  5081.6 1776.19  5156.9 1779.44  5174.2 1780.91
  5199.3 1784.83  5204.3 1783.89  5301.4 1790.21  5349.9 1791.80  5395.2 1792.24
  5425.3 1795.35  5475.6 1796.75  5666.4 1797.88  5686.5 1798.84  5753.6 1798.43
#Mann=7,-1,0
  2638.0   0.045       0  2985.2    0.07       0  3057.8   0.045       0
  4708.8    0.07       0  4993.3    0.07       0  5006.8    0.07       0
  5349.9   0.063       0
Bank Sta=4993.3,5006.8
Exp/Cntr=0.3,0.1

Type RM Length L Ch R = 1,45972,376,376,376
BEGIN DESCRIPTION:
Cat Claw Creek 40.0
END DESCRIPTION:
XS GIS Cut Line= 3
      1572125.85      6827091.73      1574459.44      6827839.62
      1575188.26      6827950.44
#Sta/Elev= 30
  2549.5 1790.81  2618.0 1791.14  2768.9 1787.79  3161.0 1785.29  4154.6 1781.38
  4229.4 1779.79  4711.3 1777.51  4909.4 1776.65  4984.8 1774.39  4993.2 1772.97
  4993.7 1772.47  5006.8 1772.97  5015.7 1772.97  5036.0 1778.02  5054.3 1779.52
  5085.2 1779.64  5147.2 1791.00  5258.5 1792.43  5299.0 1796.82  5329.3 1796.64
  5339.4 1798.26  5349.5 1798.57  5359.9 1795.80  5369.8 1795.36  5481.0 1794.42
  5518.2 1795.97  5619.4 1795.90  5653.0 1794.23  5673.2 1795.59  5737.2 1795.54
#Mann=8,-1,0
  2549.5   0.045       0  2768.9    0.07       0  3161.0   0.045       0
  4711.3    0.07       0  4993.2    0.07       0  5006.8    0.07       0
  5054.3   0.035       0  5518.2   0.063       0
Bank Sta=4993.2,5006.8
Exp/Cntr=0.3,0.1

Type RM Length L Ch R = 1,45596,571,571,571
BEGIN DESCRIPTION:
Cat Claw Creek 39.5
END DESCRIPTION:
XS GIS Cut Line= 3
      1572568.00      6828112.19      1574860.61      6828188.16
      1575874.07      6828175.88
#Sta/Elev= 30
  3161.3 1782.31  3748.6 1782.13  4092.6 1779.06  4910.7 1778.22  4929.3 1778.34
  4979.3 1774.94  4989.3 1773.45  4993.2 1771.57  4993.7 1771.07  5006.8 1771.57
  5019.3 1773.15  5039.8 1772.54  5192.1 1784.17  5279.5 1790.82  5301.9 1787.44
  5341.0 1788.49  5369.5 1788.37  5399.5 1794.13  5465.4 1791.40  5499.6 1790.20
  5629.6 1792.36  5699.6 1791.46  5789.6 1793.72  5829.6 1793.64  5849.6 1791.96
  5889.8 1792.85  5956.9 1794.07  6309.6 1792.89  6379.6 1794.08  6468.7 1792.94
#Mann=10,-1,0
  3161.3   0.045       0  4910.7    0.07       0  4993.2    0.07       0
  5006.8    0.07       0  5039.8    0.16       0  5192.1   0.035       0
  5341.0    0.16       0  5465.4   0.063       0  5889.8   0.094       0
  5956.9   0.063       0
Bank Sta=4993.2,5006.8
Exp/Cntr=0.3,0.1

Type RM Length L Ch R = 1,45025,611,611,611
BEGIN DESCRIPTION:
Cat Claw Creek 39.0
END DESCRIPTION:
XS GIS Cut Line= 3
      1572508.18      6828632.35      1574800.82      6828708.32
      1575814.25      6828696.03
#Sta/Elev= 30
  3052.5 1781.35  3769.7 1780.75  4230.0 1777.45  4808.1 1776.69  4907.1 1777.42
  4940.4 1776.60  4993.2 1770.99  4993.7 1770.49  5006.9 1770.99  5020.4 1774.09
  5050.4 1775.12  5070.4 1779.40  5105.0 1780.49  5160.5 1780.50  5346.0 1786.43
  5490.6 1785.98  5530.6 1789.29  5630.6 1790.06  5650.6 1788.44  5700.6 1791.20
  5760.6 1791.46  5785.3 1791.26  5810.6 1788.67  5845.9 1789.12  5849.0 1789.33
  5880.6 1791.87  6116.1 1792.37  6204.9 1792.44  6270.6 1790.46  6359.9 1792.57
#Mann=10,-1,0
  3052.5   0.045       0  4808.1   0.063       0  4907.1    0.07       0
  4993.2    0.07       0  5006.9    0.07       0  5105.0   0.063       0
  5845.9   0.094       0  5849.0   0.063       0  6116.1   0.094       0
  6204.9   0.063       0
Bank Sta=4993.2,5006.9
Exp/Cntr=0.3,0.1

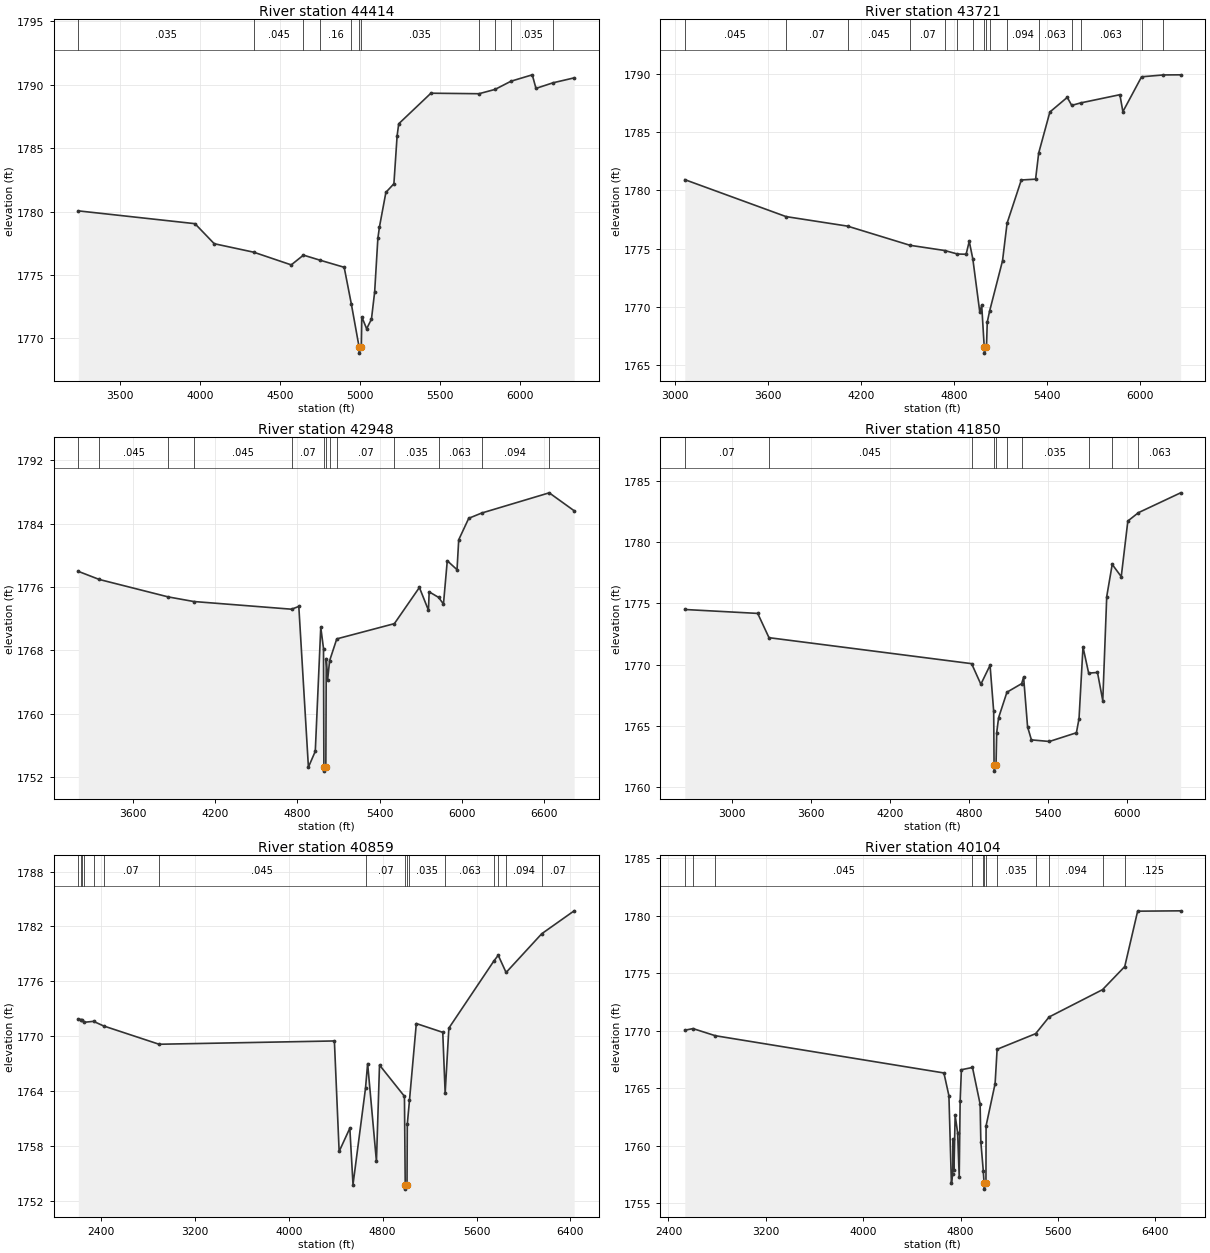
Type RM Length L Ch R = 1,44414,693,693,693
BEGIN DESCRIPTION:
Cat Claw Creek 38.0
END DESCRIPTION:
XS GIS Cut Line= 3
      1572447.96      6829113.56      1574553.61      6829217.76
      1575531.27      6829089.19
#Sta/Elev= 30
  3241.1 1780.06  3969.0 1779.05  4089.2 1777.47  4335.8 1776.80  4569.8 1775.80
  4646.0 1776.57  4746.9 1776.18  4900.2 1775.61  4944.8 1772.72  4993.0 1769.34
  4993.5 1768.84  5007.1 1769.34  5010.3 1771.70  5040.3 1770.76  5070.4 1771.52
  5090.4 1773.67  5110.4 1777.89  5120.4 1778.80  5160.5 1781.52  5210.5 1782.20
  5230.6 1785.99  5240.6 1786.93  5441.5 1789.34  5741.5 1789.30  5841.7 1789.64
  5941.9 1790.29  6074.0 1790.79  6097.1 1789.72  6203.0 1790.16  6335.4 1790.55
#Mann=11,-1,0
  3241.1   0.035       0  4335.8   0.045       0  4646.0    0.07       0
  4746.9    0.16       0  4944.8   0.035       0  4993.0   0.035       0
  5007.1   0.035       0  5741.5   0.063       0  5841.7   0.094       0
  5941.9   0.035       0  6203.0   0.063       0
Bank Sta=4993,5007.1
Exp/Cntr=0.3,0.1

Type RM Length L Ch R = 1,43721,773,773,773
BEGIN DESCRIPTION:
Cat Claw Creek 37.0
END DESCRIPTION:
XS GIS Cut Line= 3
      1572068.04      6829572.71      1573998.56      6829735.73
      1575228.74      6829469.28
#Sta/Elev= 30
  3062.6 1780.93  3715.1 1777.75  4111.4 1776.93  4514.5 1775.28  4738.3 1774.83
  4820.0 1774.53  4876.0 1774.51  4896.1 1775.62  4919.2 1774.11  4964.4 1769.50
  4976.4 1770.13  4992.9 1766.50  4993.4 1766.00  5007.2 1766.50  5012.3 1768.67
  5026.9 1769.59  5110.7 1773.95  5140.0 1777.18  5231.7 1780.90  5323.8 1780.97
  5343.8 1783.22  5415.9 1786.75  5527.9 1788.01  5556.7 1787.32  5613.5 1787.53
  5867.2 1788.24  5886.5 1786.78  6007.0 1789.78  6147.3 1789.94  6258.7 1789.95
#Mann=16,-1,0
  3062.6   0.045       0  3715.1    0.07       0  4111.4   0.045       0
  4514.5    0.07       0  4738.3   0.045       0  4820.0    0.07       0
  4919.2   0.035       0  4992.9   0.035       0  5007.2   0.035       0
  5026.9    0.07       0  5140.0   0.094       0  5343.8   0.063       0
  5556.7   0.094       0  5613.5   0.063       0  6007.0   0.094       0
  6147.3   0.063       0
Bank Sta=4992.9,5007.2
Exp/Cntr=0.3,0.1

Type RM Length L Ch R = 1,42948,1098,1098,1098
BEGIN DESCRIPTION:
Cat Claw Creek 36.0
END DESCRIPTION:
XS GIS Cut Line= 3
      1572208.31      6830233.26      1574368.90      6830336.78
      1575761.46      6829917.76
#Sta/Elev= 30
  3201.5 1777.97  3354.1 1776.95  3857.4 1774.75  4043.7 1774.17  4757.2 1773.20
  4810.0 1773.55  4880.1 1753.29  4930.2 1755.29  4970.2 1770.92  4990.2 1768.24
  4992.9 1753.29  4993.4 1752.79  5007.2 1753.29  5010.3 1766.98  5020.3 1764.31
  5034.7 1766.71  5087.0 1769.46  5507.2 1771.38  5689.7 1775.94  5755.8 1773.07
  5761.0 1775.39  5829.8 1774.69  5865.3 1773.85  5893.1 1779.31  5964.3 1778.18
  5976.6 1781.95  6049.7 1784.66  6143.7 1785.32  6636.9 1787.87  6818.8 1785.61
#Mann=13,-1,0
  3201.5    0.07       0  3354.1   0.045       0  3857.4    0.07       0
  4043.7   0.045       0  4757.2    0.07       0  4992.9    0.07       0
  5007.2    0.07       0  5034.7    0.16       0  5087.0    0.07       0
  5507.2   0.035       0  5829.8   0.063       0  6143.7   0.094       0
  6636.9   0.063       0
Bank Sta=4992.9,5007.2
Exp/Cntr=0.3,0.1

Type RM Length L Ch R = 1,41850,991,991,991
BEGIN DESCRIPTION:
Cat Claw Creek 35.0
END DESCRIPTION:
XS GIS Cut Line= 4
      1572172.75      6830934.92      1574455.63      6831127.86
      1574619.75      6831034.96      1575905.00      6830938.00
#Sta/Elev= 30
  2642.0 1774.50  3196.2 1774.18  3281.9 1772.20  4821.9 1770.08  4892.2 1768.40
  4962.1 1769.95  4989.7 1766.19  4992.6 1761.81  4993.1 1761.31  5007.4 1761.81
  5012.7 1764.46  5027.0 1765.67  5090.4 1767.75  5202.3 1768.45  5217.1 1768.98
  5247.2 1764.93  5276.4 1763.86  5413.1 1763.73  5618.3 1764.44  5638.3 1765.59
  5668.4 1771.44  5711.5 1769.31  5778.7 1769.36  5818.8 1767.06  5848.9 1775.56
  5890.6 1778.18  5959.2 1777.18  6009.4 1781.72  6089.6 1782.40  6410.5 1784.02
#Mann=10,-1,0
  2642.0    0.07       0  3281.9   0.045       0  4821.9    0.16       0
  4992.6    0.07       0  5007.4    0.16       0  5090.4    0.07       0
  5202.3   0.035       0  5711.5   0.063       0  5890.6   0.094       0
  6089.6   0.063       0
Bank Sta=4992.6,5007.4
Exp/Cntr=0.3,0.1

Type RM Length L Ch R = 1,40859,755,755,755
BEGIN DESCRIPTION:
Cat Claw Creek 34.0
END DESCRIPTION:
XS GIS Cut Line= 3
      1572178.19      6831376.37      1575147.23      6831833.67
      1576320.91      6831495.08
#Sta/Elev= 30
  2206.5 1771.91  2231.4 1771.84  2236.7 1771.81  2258.8 1771.55  2336.0 1771.65
  2421.4 1771.15  2894.6 1769.15  4388.7 1769.51  4429.2 1757.45  4520.3 1759.99
  4547.4 1753.84  4653.9 1764.35  4672.0 1767.04  4747.1 1756.36  4773.2 1766.88
  4985.7 1763.47  4992.4 1753.84  4992.9 1753.34  5007.6 1753.84  5010.0 1760.41
  5028.6 1763.03  5086.9 1771.41  5312.3 1770.45  5332.7 1763.80  5364.3 1770.91
  5748.1 1778.24  5785.0 1778.86  5852.0 1776.98  6155.8 1781.21  6432.1 1783.71
#Mann=16,-1,0
  2206.5   0.045       0  2231.4    0.07       0  2236.7   0.035       0
  2258.8   0.045       0  2336.0   0.035       0  2421.4    0.07       0
  2894.6   0.045       0  4653.9    0.07       0  4992.4    0.07       0
  5007.6    0.07       0  5028.6   0.035       0  5332.7   0.063       0
  5748.1   0.094       0  5785.0   0.063       0  5852.0   0.094       0
  6155.8    0.07       0
Bank Sta=4992.4,5007.6
Exp/Cntr=0.3,0.1

Type RM Length L Ch R = 1,40104,656,656,656
BEGIN DESCRIPTION:
Cat Claw Creek 33.0
END DESCRIPTION:
XS GIS Cut Line= 3
      1572349.32      6831854.76      1574956.37      6832446.32
      1576238.51      6831885.37
#Sta/Elev= 30
  2534.0 1770.05  2601.4 1770.19  2785.1 1769.57  4662.4 1766.33  4703.5 1764.35
  4724.0 1756.72  4734.2 1757.51  4739.9 1760.60  4745.0 1757.91  4754.7 1762.64
  4775.2 1761.12  4788.1 1757.29  4795.7 1763.85  4806.0 1766.61  4897.1 1766.81
  4959.8 1763.62  4965.7 1760.34  4986.1 1757.77  4992.4 1756.72  4992.9 1756.22
  5007.7 1756.72  5008.8 1761.73  5082.9 1765.40  5099.4 1768.39  5416.0 1769.75
  5526.2 1771.20  5965.4 1773.58  6147.8 1775.59  6253.7 1780.41  6606.8 1780.44
#Mann=12,-1,0
  2534.0   0.035       0  2601.4    0.07       0  2785.1   0.045       0
  4897.1    0.07       0  4986.1    0.16       0  4992.4    0.07       0
  5007.7    0.16       0  5099.4   0.035       0  5416.0   0.063       0
  5526.2   0.094       0  5965.4   0.063       0  6147.8   0.125       0
Bank Sta=4992.4,5007.7
Exp/Cntr=0.3,0.1

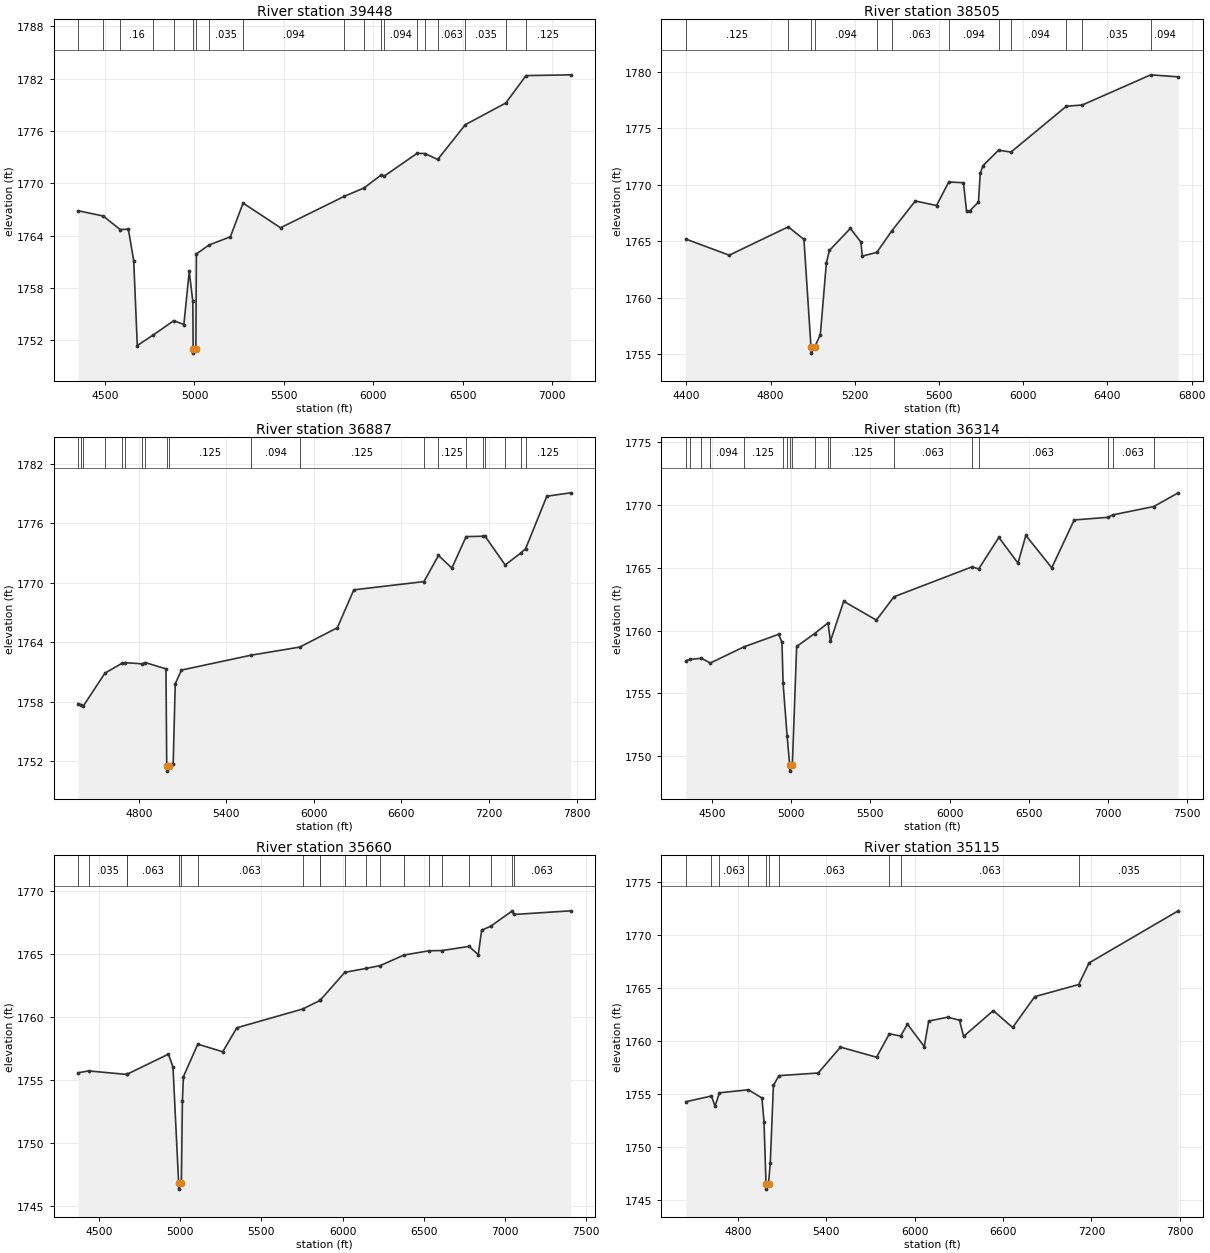
Type RM Length L Ch R = 1,39448,943,943,943
BEGIN DESCRIPTION:
Cat Claw Creek 32.0
END DESCRIPTION:
XS GIS Cut Line= 4
      1574130.76      6833119.96      1574273.77      6833029.31
      1575095.01      6832977.05      1576660.28      6832166.08
#Sta/Elev= 30
  4349.1 1766.86  4488.6 1766.26  4584.1 1764.71  4629.9 1764.75  4659.9 1761.14
  4680.0 1751.41  4768.3 1752.61  4883.9 1754.26  4940.5 1753.82  4970.6 1759.90
  4990.6 1756.49  4992.4 1751.04  4992.9 1750.54  5007.7 1751.04  5010.6 1761.91
  5080.9 1762.93  5201.0 1763.88  5271.8 1767.74  5481.3 1764.91  5836.8 1768.50
  5949.9 1769.49  6043.1 1770.94  6063.0 1770.85  6245.4 1773.44  6289.3 1773.42
  6360.8 1772.74  6515.6 1776.73  6741.8 1779.21  6854.9 1782.35  7104.2 1782.44
#Mann=19,-1,0
  4349.1   0.035       0  4488.6    0.07       0  4584.1    0.16       0
  4768.3    0.07       0  4883.9    0.16       0  4992.4    0.07       0
  5007.7    0.16       0  5080.9   0.035       0  5271.8   0.094       0
  5836.8   0.063       0  5949.9   0.094       0  6043.1   0.063       0
  6063.0   0.094       0  6245.4   0.063       0  6289.3   0.094       0
  6360.8   0.063       0  6515.6   0.035       0  6741.8   0.063       0
  6854.9   0.125       0
Bank Sta=4992.4,5007.7
Exp/Cntr=0.3,0.1

Type RM Length L Ch R = 1,38505,1618,1618,1618
BEGIN DESCRIPTION:
Cat Claw Creek 31.0
END DESCRIPTION:
XS GIS Cut Line= 4
      1574947.82      6833743.06      1575098.75      6833716.51
      1575551.01      6833335.12      1576850.35      6832410.67
#Sta/Elev= 30
  4396.8 1765.20  4603.0 1763.77  4883.5 1766.28  4958.0 1765.17  4991.7 1755.60
  4992.2 1755.10  5008.4 1755.60  5036.0 1756.74  5064.6 1763.08  5078.9 1764.19
  5178.5 1766.14  5228.9 1764.93  5235.1 1763.69  5304.3 1764.02  5376.0 1765.94
  5487.2 1768.57  5588.0 1768.17  5645.9 1770.25  5715.9 1770.19  5730.7 1767.67
  5745.4 1767.69  5787.2 1768.47  5795.8 1771.04  5809.3 1771.71  5882.8 1773.07
  5941.6 1772.90  6205.0 1776.96  6280.6 1777.07  6606.0 1779.74  6736.3 1779.56
#Mann=12,-1,0
  4396.8   0.125       0  4883.5   0.094       0  4991.7   0.035       0
  5008.4   0.094       0  5304.3   0.094       0  5376.0   0.063       0
  5645.9   0.094       0  5882.8   0.035       0  5941.6   0.094       0
  6205.0   0.125       0  6280.6   0.035       0  6606.0   0.094       0
Bank Sta=4991.7,5008.4
Exp/Cntr=0.3,0.1

Type RM Length L Ch R = 1,36887,573,573,573
BEGIN DESCRIPTION:
Cat Claw Creek 30.0
END DESCRIPTION:
XS GIS Cut Line= 3
      1574955.97      6835309.59      1575611.43      6834684.90
      1577329.28      6832912.29
#Sta/Elev= 30
  4384.7 1757.82  4402.1 1757.72  4420.8 1757.59  4568.0 1760.89  4683.1 1761.87
  4706.0 1761.95  4823.6 1761.83  4844.0 1761.96  4986.4 1761.32  4991.6 1751.50
  4992.1 1751.00  5008.4 1751.50  5035.8 1751.76  5049.9 1759.82  5092.4 1761.20
  5571.8 1762.71  5903.1 1763.52  6160.4 1765.47  6273.6 1769.30  6754.0 1770.13
  6853.6 1772.77  6945.3 1771.50  7043.0 1774.67  7159.8 1774.71  7171.8 1774.73
  7310.5 1771.81  7416.2 1773.00  7450.5 1773.45  7596.0 1778.75  7758.6 1779.09
#Mann=20,-1,0
  4384.7   0.094       0  4402.1   0.125       0  4420.8   0.094       0
  4568.0   0.125       0  4683.1   0.094       0  4706.0   0.125       0
  4823.6   0.094       0  4844.0   0.125       0  4991.6    0.07       0
  5008.4   0.125       0  5571.8   0.094       0  5903.1   0.125       0
  6754.0   0.094       0  6853.6   0.125       0  7043.0   0.094       0
  7159.8   0.125       0  7171.8   0.094       0  7310.5   0.125       0
  7416.2   0.094       0  7450.5   0.125       0
Bank Sta=4991.6,5008.4
Exp/Cntr=0.3,0.1

Type RM Length L Ch R = 1,36314,654,654,654
BEGIN DESCRIPTION:
Cat Claw Creek 29.0
END DESCRIPTION:
XS GIS Cut Line= 4
      1575173.07      6835790.53      1575318.67      6835685.88
      1575838.16      6835214.57      1577528.06      6833765.73
#Sta/Elev= 30
  4336.3 1757.60  4365.3 1757.71  4435.1 1757.79  4490.9 1757.41  4701.2 1758.69
  4922.1 1759.70  4943.0 1759.06  4950.0 1755.81  4975.5 1751.61  4991.6 1749.30
  4992.1 1748.80  5008.5 1749.30  5035.6 1758.73  5149.1 1759.76  5233.5 1760.61
  5248.9 1759.15  5332.5 1762.33  5538.8 1760.83  5649.7 1762.69  6141.7 1765.07
  6184.2 1764.91  6311.5 1767.42  6432.2 1765.37  6481.6 1767.58  6645.2 1765.00
  6786.7 1768.81  7000.6 1769.02  7029.2 1769.21  7289.0 1769.88  7443.0 1770.97
#Mann=18,-1,0
  4336.3   0.125       0  4365.3   0.094       0  4435.1   0.125       0
  4490.9   0.094       0  4701.2   0.125       0  4950.0   0.063       0
  4975.5   0.035       0  4991.6   0.035       0  5008.5   0.035       0
  5149.1   0.063       0  5233.5   0.035       0  5248.9   0.125       0
  5649.7   0.063       0  6141.7   0.035       0  6184.2   0.063       0
  7000.6   0.035       0  7029.2   0.063       0  7289.0   0.035       0
Bank Sta=4991.6,5008.5
Exp/Cntr=0.3,0.1

Type RM Length L Ch R = 1,35660,545,545,545
BEGIN DESCRIPTION:
Cat Claw Creek 28.0
END DESCRIPTION:
XS GIS Cut Line= 4
      1575524.91      6836390.98      1575733.16      6836182.83
      1576162.75      6835639.17      1577744.37      6834347.48
#Sta/Elev= 30
  4373.5 1755.56  4437.5 1755.71  4671.6 1755.43  4672.0 1755.43  4929.0 1757.04
  4957.0 1756.01  4991.6 1746.83  4992.1 1746.33  5008.5 1746.83  5014.8 1753.29
  5021.1 1755.26  5109.5 1757.83  5263.2 1757.23  5349.6 1759.13  5754.5 1760.62
  5862.8 1761.31  5864.1 1761.34  6013.9 1763.53  6144.8 1763.84  6232.7 1764.07
  6377.3 1764.90  6531.9 1765.24  6613.2 1765.26  6778.7 1765.59  6835.0 1764.93
  6855.8 1766.87  6912.9 1767.20  7040.3 1768.37  7054.5 1768.12  7402.9 1768.41
#Mann=20,-1,0
  4373.5   0.063       0  4437.5   0.035       0  4671.6   0.094       0
  4672.0   0.063       0  4991.6   0.063       0  5008.5   0.063       0
  5109.5   0.063       0  5754.5   0.035       0  5862.8   0.063       0
  5864.1   0.035       0  6013.9   0.063       0  6144.8   0.035       0
  6232.7   0.063       0  6377.3   0.094       0  6531.9   0.125       0
  6613.2   0.063       0  6778.7   0.094       0  6912.9   0.063       0
  7040.3   0.094       0  7054.5   0.063       0
Bank Sta=4991.6,5008.5
Exp/Cntr=0.3,0.1

Type RM Length L Ch R = 1,35115,1118,1118,1118
BEGIN DESCRIPTION:
Cat Claw Creek 27.6
END DESCRIPTION:
XS GIS Cut Line= 4
      1575872.01      6836594.61      1576027.79      6836567.67
      1576564.26      6836049.85      1578585.67      6834687.95
#Sta/Elev= 30
  4447.4 1754.31  4621.5 1754.85  4645.6 1753.89  4675.5 1755.15  4872.4 1755.44
  4963.9 1754.66  4978.0 1752.44  4991.6 1746.57  4992.1 1746.07  5008.5 1746.57
  5020.5 1748.53  5041.8 1755.85  5079.5 1756.77  5345.9 1757.02  5496.7 1759.46
  5741.5 1758.51  5828.8 1760.72  5904.7 1760.50  5951.4 1761.62  6065.4 1759.51
  6095.4 1761.92  6224.3 1762.28  6304.6 1762.00  6332.3 1760.47  6533.7 1762.90
  6665.1 1761.31  6815.0 1764.22  7113.1 1765.36  7183.8 1767.40  7788.5 1772.31
#Mann=10,-1,0
  4447.4   0.063       0  4621.5   0.094       0  4675.5   0.063       0
  4872.4   0.035       0  4991.6   0.035       0  5008.5   0.035       0
  5079.5   0.063       0  5828.8   0.035       0  5904.7   0.063       0
  7113.1   0.035       0
Bank Sta=4991.6,5008.5
Exp/Cntr=0.3,0.1