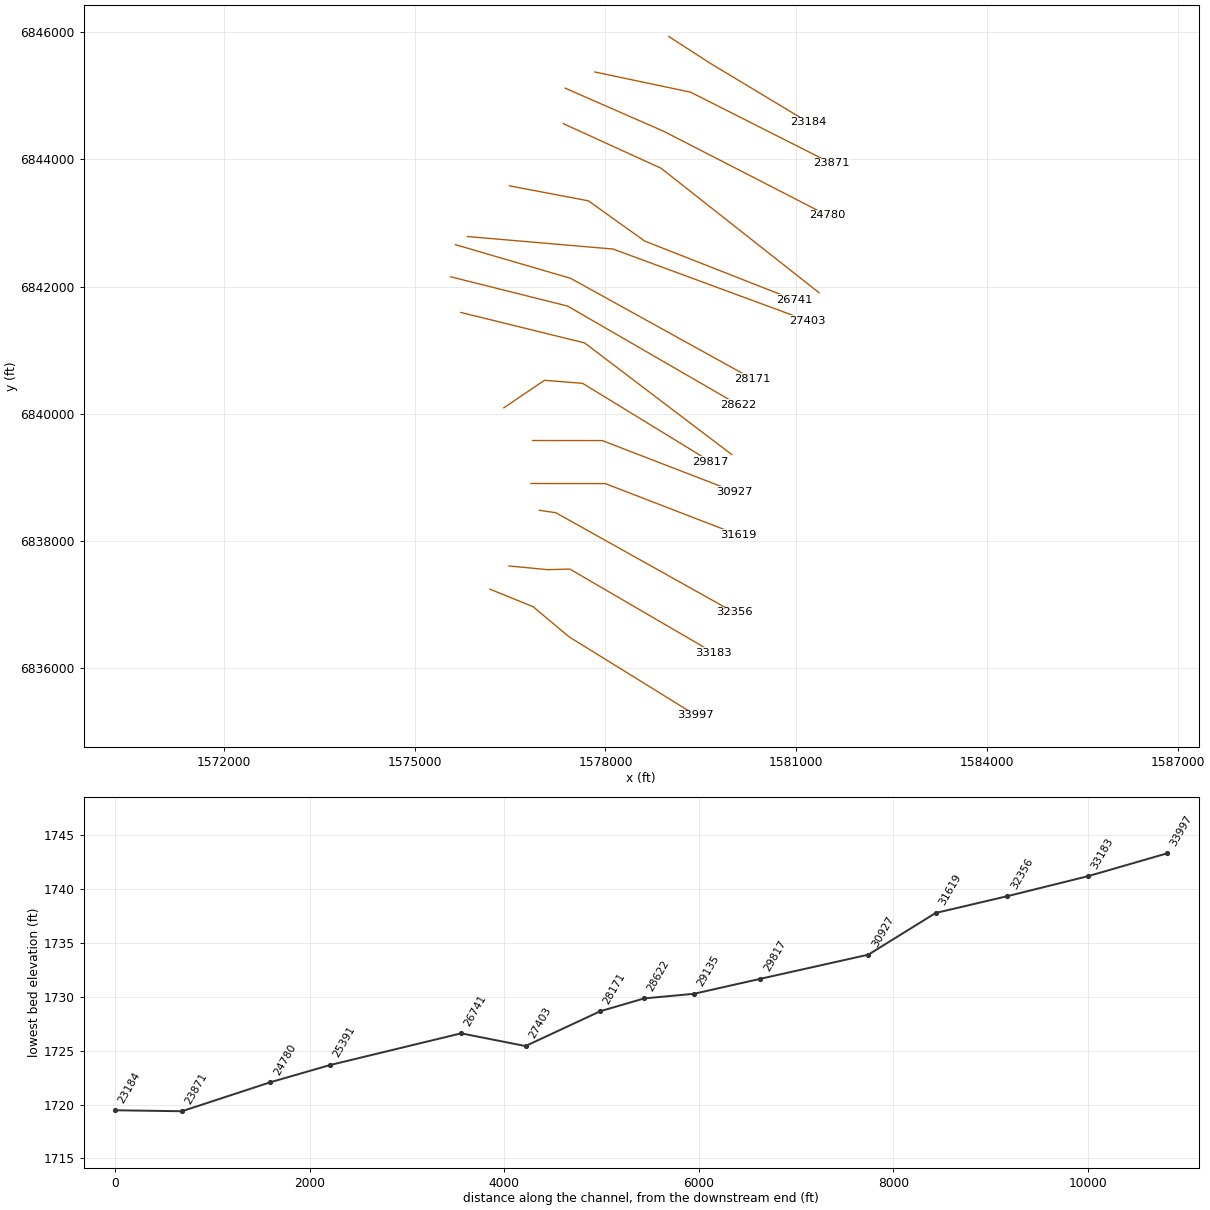
HEC-RAS study Cat Claw Creek.prj: Cat Claw Creek Base Level Engineering

--- Cat Claw Creek.g01 (geometry) --- (continued)

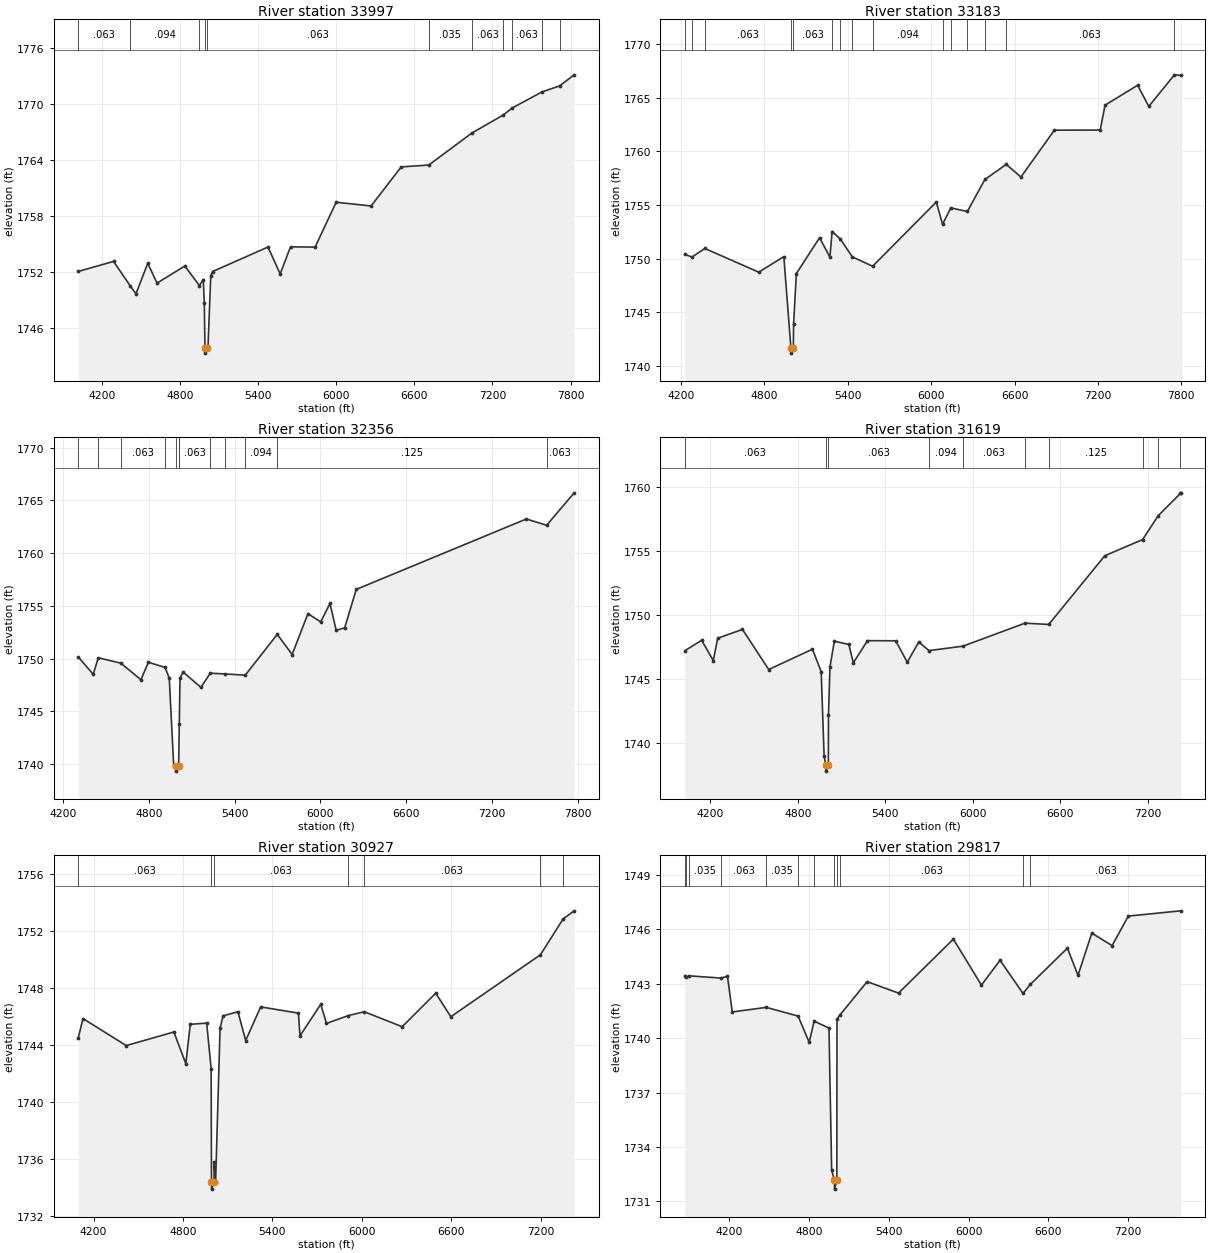
Type RM Length L Ch R = 1,33997,814,814,814
BEGIN DESCRIPTION:
Cat Claw Creek 27.3
END DESCRIPTION:
XS GIS Cut Line= 4
      1576184.41      6837242.73      1576861.75      6836968.24
      1577428.80      6836493.91      1579418.17      6835262.64
#Sta/Elev= 30
  4018.4 1752.05  4289.1 1753.12  4415.9 1750.53  4461.4 1749.66  4551.7 1752.92
  4623.3 1750.80  4836.8 1752.63  4948.7 1750.53  4978.6 1751.18  4986.4 1748.62
  4991.5 1743.81  4992.0 1743.31  5008.5 1743.81  5014.2 1743.81  5035.9 1751.60
  5050.2 1752.04  5475.7 1754.66  5569.3 1751.78  5648.7 1754.68  5837.5 1754.65
  5999.5 1759.45  6267.7 1759.05  6499.3 1763.23  6711.2 1763.43  7041.9 1766.85
  7283.4 1768.78  7350.7 1769.52  7580.5 1771.25  7716.8 1771.90  7828.1 1773.08
#Mann=11,-1,0
  4018.4   0.063       0  4415.9   0.094       0  4948.7   0.063       0
  4991.5   0.063       0  5008.5   0.063       0  6711.2   0.035       0
  7041.9   0.063       0  7283.4   0.035       0  7350.7   0.063       0
  7580.5   0.094       0  7716.8   0.035       0
Bank Sta=4991.5,5008.5
Exp/Cntr=0.3,0.1

Type RM Length L Ch R = 1,33183,827,827,827
BEGIN DESCRIPTION:
Cat Claw Creek 27.0
END DESCRIPTION:
XS GIS Cut Line= 4
      1576485.32      6837607.57      1577089.07      6837549.85
      1577441.64      6837558.58      1579694.88      6836245.91
#Sta/Elev= 30
  4228.1 1750.40  4280.1 1750.15  4372.1 1750.95  4760.2 1748.74  4940.6 1750.19
  4991.3 1741.69  4991.8 1741.19  5008.8 1741.69  5010.6 1743.90  5030.6 1748.61
  5197.7 1751.95  5272.1 1750.14  5287.8 1752.53  5347.7 1751.82  5432.7 1750.17
  5579.2 1749.29  6037.3 1755.28  6082.4 1753.21  6141.5 1754.73  6260.6 1754.40
  6387.0 1757.38  6540.4 1758.79  6646.1 1757.61  6886.8 1761.98  7216.5 1761.99
  7251.2 1764.31  7485.7 1766.17  7565.9 1764.20  7750.6 1767.14  7795.0 1767.09
#Mann=15,-1,0
  4228.1   0.063       0  4280.1   0.094       0  4372.1   0.063       0
  4991.3   0.063       0  5008.8   0.063       0  5287.8   0.063       0
  5347.7   0.094       0  5432.7   0.063       0  5579.2   0.094       0
  6082.4   0.063       0  6141.5   0.094       0  6260.6   0.063       0
  6387.0   0.094       0  6540.4   0.063       0  7750.6   0.035       0
Bank Sta=4991.3,5008.8
Exp/Cntr=0.3,0.1

Type RM Length L Ch R = 1,32356,737,737,737
BEGIN DESCRIPTION:
Cat Claw Creek 26.6
END DESCRIPTION:
XS GIS Cut Line= 3
      1576961.90      6838482.90      1577221.03      6838444.27
      1580020.93      6836878.82
#Sta/Elev= 30
  4306.8 1750.15  4411.0 1748.52  4446.3 1750.08  4604.3 1749.57  4745.2 1748.00
  4796.8 1749.66  4914.3 1749.16  4943.0 1748.16  4974.3 1739.84  4991.2 1739.84
  4991.7 1739.34  5008.8 1739.84  5013.3 1743.76  5018.3 1748.12  5040.0 1748.73
  5164.5 1747.28  5230.3 1748.62  5333.2 1748.55  5474.8 1748.43  5699.0 1752.30
  5802.9 1750.39  5913.8 1754.26  6002.8 1753.48  6067.9 1755.23  6111.3 1752.69
  6170.6 1752.91  6251.7 1756.56  7441.7 1763.23  7584.1 1762.64  7776.6 1765.71
#Mann=12,-1,0
  4306.8   0.063       0  4446.3   0.035       0  4604.3   0.063       0
  4914.3   0.035       0  4991.2   0.035       0  5008.8   0.035       0
  5013.3   0.063       0  5230.3   0.094       0  5333.2   0.063       0
  5474.8   0.094       0  5699.0   0.125       0  7584.1   0.063       0
Bank Sta=4991.2,5008.8
Exp/Cntr=0.3,0.1

Type RM Length L Ch R = 1,31619,692,692,692
BEGIN DESCRIPTION:
Cat Claw Creek 26.3
END DESCRIPTION:
XS GIS Cut Line= 3
      1576829.54      6838903.69      1577997.54      6838902.39
      1580080.32      6838098.33
#Sta/Elev= 30
  4024.3 1747.21  4139.8 1748.03  4219.8 1746.44  4249.8 1748.19  4419.8 1748.88
  4599.8 1745.74  4899.8 1747.33  4959.8 1745.57  4979.8 1738.95  4991.2 1738.28
  4991.7 1737.78  5008.8 1738.28  5009.8 1742.18  5019.8 1745.93  5049.8 1747.96
  5149.8 1747.70  5179.8 1746.26  5277.3 1748.00  5471.0 1747.99  5550.1 1746.31
  5629.1 1747.90  5699.1 1747.22  5932.3 1747.57  6357.2 1749.37  6520.5 1749.27
  6904.7 1754.65  7164.1 1755.92  7271.4 1757.79  7423.8 1759.54  7424.9 1759.58
#Mann=10,-1,0
  4024.3   0.063       0  4991.2   0.063       0  5008.8   0.063       0
  5699.1   0.094       0  5932.3   0.063       0  6357.2   0.094       0
  6520.5   0.125       0  7164.1   0.094       0  7271.4   0.063       0
  7423.8   0.094       0
Bank Sta=4991.2,5008.8
Exp/Cntr=0.3,0.1

Type RM Length L Ch R = 1,30927,1110,1110,1110
BEGIN DESCRIPTION:
Cat Claw Creek 26.0
END DESCRIPTION:
XS GIS Cut Line= 3
      1576853.56      6839579.44      1577950.62      6839578.21
      1580031.84      6838774.73
#Sta/Elev= 30
  4097.5 1744.53  4128.9 1745.86  4418.9 1743.97  4738.9 1744.92  4818.9 1742.70
  4848.9 1745.46  4958.9 1745.54  4988.9 1742.36  4991.2 1734.41  4991.7 1733.91
  5008.8 1734.41  5008.9 1735.78  5018.9 1734.41  5048.9 1745.20  5068.9 1746.05
  5168.9 1746.34  5220.7 1744.32  5321.3 1746.68  5574.9 1746.24  5585.2 1744.65
  5724.5 1746.86  5763.2 1745.52  5909.4 1746.07  6016.7 1746.34  6271.2 1745.29
  6496.3 1747.64  6597.7 1745.99  7199.2 1750.33  7351.3 1752.84  7425.5 1753.41
#Mann=7,-1,0
  4097.5   0.063       0  4991.2   0.063       0  5008.8   0.063       0
  5909.4   0.094       0  6016.7   0.063       0  7199.2   0.094       0
  7351.3   0.063       0
Bank Sta=4991.2,5008.8
Exp/Cntr=0.3,0.1

Type RM Length L Ch R = 1,29817,682,682,682
BEGIN DESCRIPTION:
Cat Claw Creek 25.0
END DESCRIPTION:
XS GIS Cut Line= 4
      1576403.19      6840093.39      1577042.20      6840525.83
      1577642.06      6840477.95      1579653.80      6839246.07
#Sta/Elev= 30
  3864.4 1743.44  3877.0 1743.37  3899.2 1743.44  4134.6 1743.32  4185.7 1743.41
  4221.7 1741.45  4478.0 1741.70  4717.5 1741.22  4800.8 1739.77  4837.8 1740.94
  4949.8 1740.56  4969.8 1732.71  4991.1 1732.17  4991.6 1731.67  5008.9 1732.17
  5010.0 1741.05  5032.1 1741.28  5236.7 1743.12  5473.4 1742.49  5886.1 1745.47
  6097.2 1742.93  6237.5 1744.30  6410.4 1742.47  6465.2 1742.97  6744.4 1744.97
  6824.2 1743.47  6928.1 1745.80  7080.9 1745.11  7202.9 1746.74  7596.7 1747.03
#Mann=12,-1,0
  3864.4   0.035       0  3877.0   0.063       0  3899.2   0.035       0
  4134.6   0.063       0  4478.0   0.035       0  4717.5   0.063       0
  4837.8   0.035       0  4991.1   0.035       0  5008.9   0.035       0
  5032.1   0.063       0  6410.4   0.094       0  6465.2   0.063       0
Bank Sta=4991.1,5008.9
Exp/Cntr=0.3,0.1

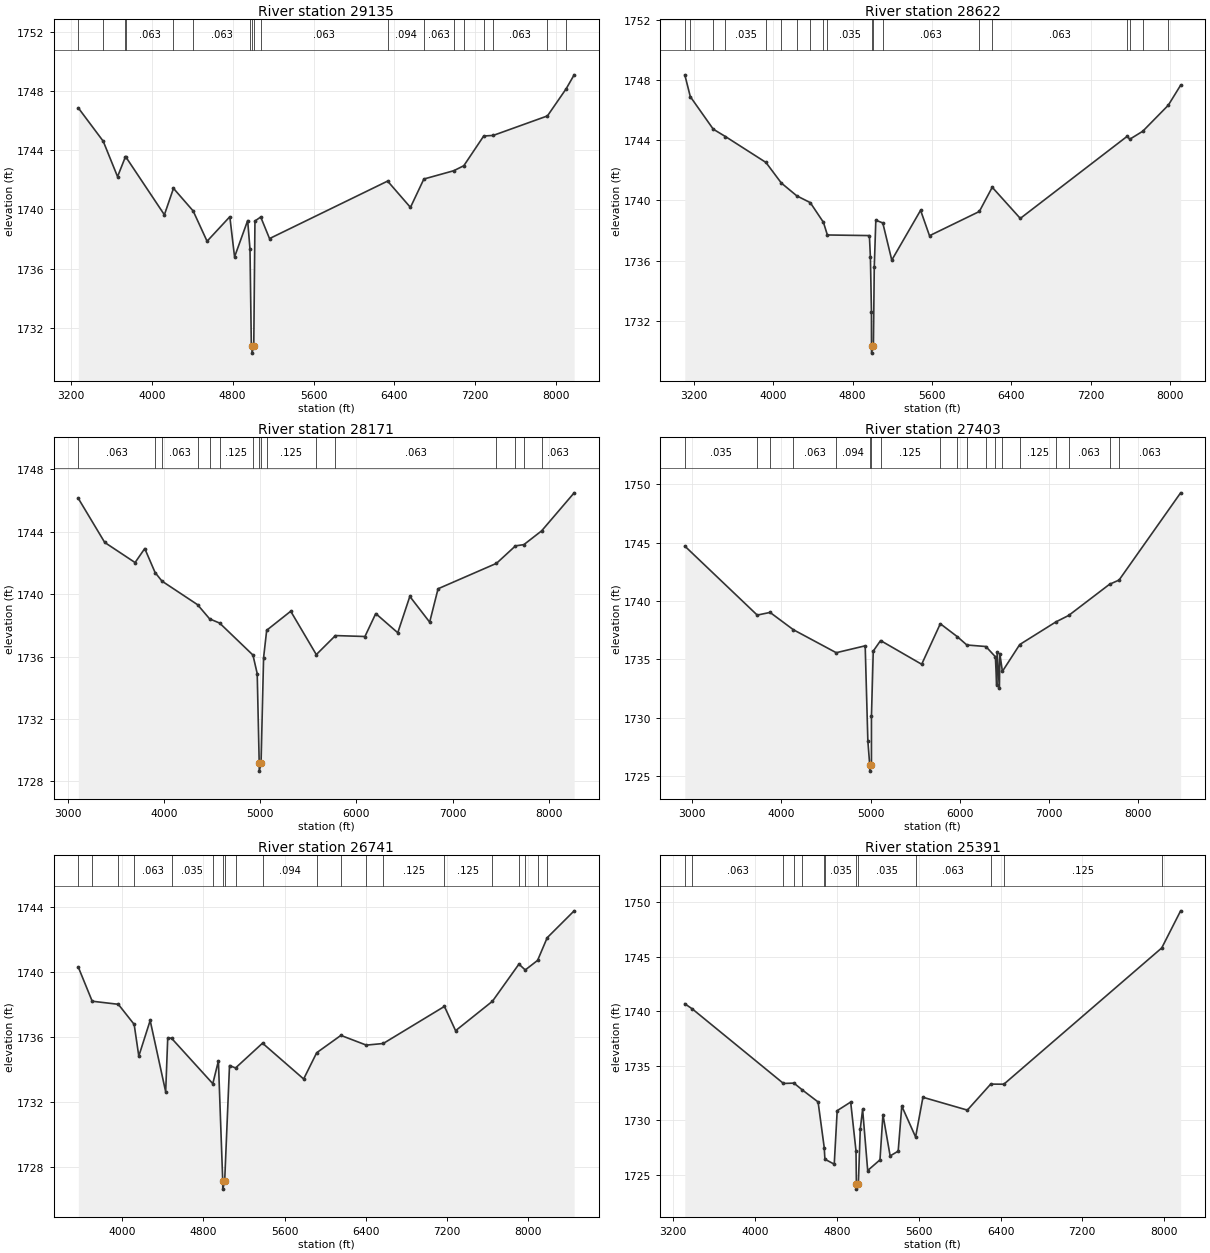
Type RM Length L Ch R = 1,29135,513,513,513
BEGIN DESCRIPTION:
Cat Claw Creek 24.0
END DESCRIPTION:
XS GIS Cut Line= 3
      1575728.17      6841591.88      1577671.76      6841113.89
      1579985.53      6839358.99
#Sta/Elev= 30
  3273.2 1746.87  3519.3 1744.62  3661.3 1742.22  3739.4 1743.57  3741.5 1743.57
  4124.7 1739.64  4214.5 1741.43  4409.3 1739.90  4546.9 1737.85  4772.1 1739.51
  4818.8 1736.79  4948.5 1739.25  4971.5 1737.32  4984.9 1730.78  4991.1 1730.78
  4991.6 1730.28  5008.9 1730.78  5020.6 1739.22  5077.7 1739.49  5164.8 1738.03
  6333.1 1741.92  6559.0 1740.14  6691.8 1742.06  6986.8 1742.62  7087.0 1742.96
  7283.8 1744.97  7377.8 1745.01  7914.4 1746.33  8099.9 1748.17  8178.7 1749.11
#Mann=18,-1,0
  3273.2   0.035       0  3519.3   0.063       0  3739.4   0.035       0
  3741.5   0.063       0  4214.5   0.035       0  4409.3   0.063       0
  4971.5   0.035       0  4991.1   0.035       0  5008.9   0.035       0
  5077.7   0.063       0  6333.1   0.094       0  6691.8   0.063       0
  6986.8   0.094       0  7087.0   0.063       0  7283.8   0.035       0
  7377.8   0.063       0  7914.4   0.094       0  8099.9   0.063       0
Bank Sta=4991.1,5008.9
Exp/Cntr=0.3,0.1

Type RM Length L Ch R = 1,28622,451,451,451
BEGIN DESCRIPTION:
Cat Claw Creek 23.0
END DESCRIPTION:
XS GIS Cut Line= 3
      1575569.82      6842152.18      1577404.94      6841692.57
      1580094.02      6840136.80
#Sta/Elev= 30
  3108.2 1748.34  3163.8 1746.89  3395.1 1744.73  3517.8 1744.24  3926.0 1742.52
  4081.6 1741.15  4237.2 1740.30  4373.1 1739.85  4505.9 1738.54  4545.5 1737.70
  4969.1 1737.66  4979.4 1736.22  4989.8 1732.61  4990.5 1730.35  4991.0 1729.85
  5009.5 1730.35  5018.3 1735.57  5034.0 1738.68  5104.2 1738.50  5194.8 1736.03
  5485.3 1739.34  5575.1 1737.65  6077.3 1739.26  6207.5 1740.87  6490.4 1738.80
  7568.7 1744.26  7593.8 1744.06  7724.5 1744.59  7982.3 1746.32  8106.7 1747.65
#Mann=19,-1,0
  3108.2   0.063       0  3163.8   0.035       0  3395.1   0.063       0
  3517.8   0.035       0  3926.0   0.063       0  4081.6   0.035       0
  4237.2   0.063       0  4373.1   0.094       0  4505.9   0.063       0
  4545.5   0.035       0  4990.5   0.035       0  5009.5   0.035       0
  5104.2   0.063       0  6077.3   0.035       0  6207.5   0.063       0
  7568.7   0.094       0  7593.8   0.063       0  7724.5   0.094       0
  7982.3   0.063       0
Bank Sta=4990.5,5009.5
Exp/Cntr=0.3,0.1

Type RM Length L Ch R = 1,28171,768,768,768
BEGIN DESCRIPTION:
Cat Claw Creek 22.0
END DESCRIPTION:
XS GIS Cut Line= 3
      1575642.00      6842657.75      1577454.13      6842127.91
      1580308.19      6840549.80
#Sta/Elev= 30
  3112.0 1746.14  3386.0 1743.32  3701.4 1742.03  3801.8 1742.93  3909.3 1741.39
  3980.8 1740.84  4350.1 1739.33  4475.6 1738.42  4579.6 1738.15  4925.5 1736.10
  4969.7 1734.91  4990.5 1729.16  4991.0 1728.66  5009.5 1729.16  5035.9 1735.93
  5068.1 1737.69  5317.7 1738.91  5583.4 1736.13  5782.1 1737.35  6088.5 1737.29
  6200.8 1738.76  6429.4 1737.53  6554.7 1739.86  6760.7 1738.21  6847.9 1740.35
  7454.7 1741.98  7652.1 1743.10  7739.1 1743.18  7923.2 1744.06  8261.3 1746.50
#Mann=16,-1,0
  3112.0   0.063       0  3909.3   0.035       0  3980.8   0.063       0
  4350.1   0.035       0  4475.6   0.063       0  4579.6   0.125       0
  4925.5   0.063       0  4990.5   0.063       0  5009.5   0.063       0
  5068.1   0.125       0  5583.4   0.094       0  5782.1   0.063       0
  7454.7   0.094       0  7652.1   0.063       0  7739.1   0.094       0
  7923.2   0.063       0
Bank Sta=4990.5,5009.5
Exp/Cntr=0.3,0.1

Type RM Length L Ch R = 1,27403,662,662,662
BEGIN DESCRIPTION:
Cat Claw Creek 21.0
END DESCRIPTION:
XS GIS Cut Line= 3
      1575830.74      6842785.32      1578119.05      6842588.87
      1581178.16      6841461.37
#Sta/Elev= 30
  2917.7 1744.70  3729.5 1738.79  3873.5 1739.02  4134.2 1737.54  4615.0 1735.57
  4939.4 1736.16  4969.5 1727.99  4990.5 1725.93  4991.0 1725.43  5009.5 1725.93
  5009.6 1730.11  5029.7 1735.71  5112.1 1736.61  5572.5 1734.58  5781.4 1738.05
  5972.4 1736.94  6079.0 1736.23  6292.2 1736.10  6398.8 1735.22  6413.0 1732.81
  6418.3 1735.64  6443.5 1732.52  6448.8 1735.48  6477.1 1733.97  6671.6 1736.27
  7077.4 1738.21  7219.9 1738.76  7678.1 1741.43  7784.7 1741.79  8474.7 1749.26
#Mann=19,-1,0
  2917.7   0.035       0  3729.5   0.063       0  3873.5   0.035       0
  4134.2   0.063       0  4615.0   0.094       0  4990.5    0.07       0
  5009.5   0.094       0  5112.1   0.125       0  5781.4   0.063       0
  5972.4   0.094       0  6079.0   0.063       0  6292.2   0.035       0
  6398.8   0.063       0  6477.1   0.035       0  6671.6   0.125       0
  7077.4   0.094       0  7219.9   0.063       0  7678.1   0.035       0
  7784.7   0.063       0
Bank Sta=4990.5,5009.5
Exp/Cntr=0.3,0.1

Type RM Length L Ch R = 1,26741,1350,1350,1350
BEGIN DESCRIPTION:
Cat Claw Creek 20.0
END DESCRIPTION:
XS GIS Cut Line= 4
      1576490.19      6843582.45      1577731.72      6843346.70
      1578616.96      6842714.38      1580971.45      6841789.00
#Sta/Elev= 30
  3568.8 1740.31  3705.3 1738.21  3962.5 1738.02  4118.5 1736.78  4164.1 1734.82
  4276.0 1737.02  4428.7 1732.62  4449.1 1735.96  4487.1 1735.92  4892.6 1733.12
  4947.7 1734.52  4990.5 1727.11  4991.0 1726.61  5009.6 1727.11  5057.1 1734.24
  5116.6 1734.09  5382.2 1735.62  5787.0 1733.41  5915.4 1735.03  6153.7 1736.10
  6404.1 1735.50  6570.5 1735.60  7173.1 1737.89  7282.9 1736.39  7646.0 1738.21
  7906.5 1740.50  7968.7 1740.14  8090.1 1740.73  8184.7 1742.13  8450.2 1743.79
#Mann=20,-1,0
  3568.8   0.035       0  3705.3   0.063       0  3962.5   0.035       0
  4118.5   0.063       0  4487.1   0.035       0  4892.6   0.063       0
  4990.5   0.063       0  5009.6   0.063       0  5116.6   0.125       0
  5382.2   0.094       0  5915.4   0.125       0  6153.7   0.125       0
  6404.1   0.094       0  6570.5   0.125       0  7173.1   0.125       0
  7646.0   0.094       0  7906.5   0.035       0  7968.7   0.063       0
  8090.1   0.094       0  8184.7   0.063       0
Bank Sta=4990.5,5009.6
Exp/Cntr=0.3,0.1

Type RM Length L Ch R = 1,25391,611,611,611
BEGIN DESCRIPTION:
Cat Claw Creek 19.0
END DESCRIPTION:
XS GIS Cut Line= 3
      1577338.90      6844559.10      1578874.63      6843858.47
      1581358.17      6841901.85
#Sta/Elev= 30
  3312.0 1740.69  3385.1 1740.22  4277.0 1733.37  4379.8 1733.40  4462.0 1732.77
  4615.7 1731.67  4675.9 1727.47  4682.4 1726.41  4773.7 1725.95  4802.6 1730.87
  4934.5 1731.66  4986.5 1727.18  4990.4 1724.16  4990.9 1723.66  5009.6 1724.16
  5028.6 1729.20  5051.2 1730.99  5100.9 1725.37  5221.1 1726.35  5250.0 1730.51
  5320.5 1726.71  5399.1 1727.15  5434.3 1731.29  5569.5 1728.45  5641.2 1732.10
  6075.8 1730.92  6304.0 1733.31  6432.8 1733.30  7977.0 1745.82  8161.7 1749.23
#Mann=13,-1,0
  3312.0   0.035       0  3385.1   0.063       0  4277.0   0.094       0
  4379.8   0.063       0  4462.0   0.035       0  4675.9   0.063       0
  4682.4   0.035       0  4990.4   0.035       0  5009.6   0.035       0
  5569.5   0.063       0  6304.0   0.094       0  6432.8   0.125       0
  7977.0   0.094       0
Bank Sta=4990.4,5009.6
Exp/Cntr=0.3,0.1

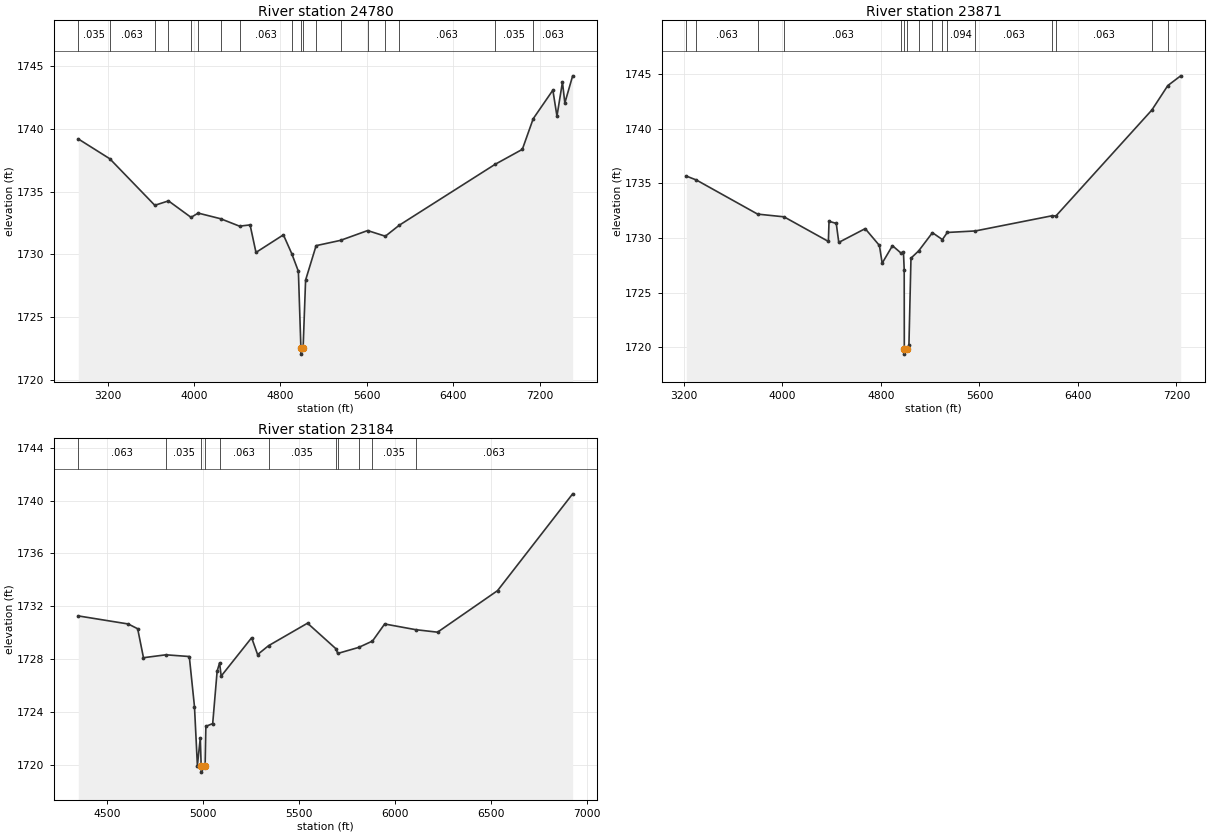
Type RM Length L Ch R = 1,24780,909,909,909
BEGIN DESCRIPTION:
Cat Claw Creek 18.5
END DESCRIPTION:
XS GIS Cut Line= 3
      1577367.61      6845117.16      1578923.17      6844436.14
      1581484.32      6843119.87
#Sta/Elev= 30
  2928.3 1739.19  3220.6 1737.61  3637.0 1733.91  3763.7 1734.26  3972.7 1732.95
  4038.4 1733.29  4246.6 1732.84  4421.4 1732.25  4519.2 1732.35  4573.8 1730.16
  4827.7 1731.56  4904.7 1730.07  4966.4 1728.66  4989.7 1722.57  4990.2 1722.07
  5010.3 1722.57  5033.2 1727.96  5130.6 1730.70  5356.4 1731.12  5607.6 1731.90
  5771.7 1731.45  5899.7 1732.32  6788.0 1737.17  7039.9 1738.36  7140.8 1740.80
  7322.7 1743.07  7360.6 1741.00  7411.4 1743.71  7433.6 1742.05  7506.0 1744.21
#Mann=18,-1,0
  2928.3   0.035       0  3220.6   0.063       0  3637.0   0.035       0
  3763.7   0.063       0  3972.7   0.035       0  4038.4   0.063       0
  4246.6   0.094       0  4421.4   0.063       0  4904.7   0.035       0
  4989.7   0.035       0  5010.3   0.035       0  5130.6   0.063       0
  5356.4   0.035       0  5607.6   0.063       0  5771.7   0.094       0
  5899.7   0.063       0  6788.0   0.035       0  7140.8   0.063       0
Bank Sta=4989.7,5010.3
Exp/Cntr=0.3,0.1

Type RM Length L Ch R = 1,23871,687,687,687
BEGIN DESCRIPTION:
Cat Claw Creek 18.0
END DESCRIPTION:
XS GIS Cut Line= 3
      1577833.24      6845371.24      1579338.04      6845054.47
      1581549.11      6843937.21
#Sta/Elev= 30
  3219.1 1735.67  3301.0 1735.31  3798.1 1732.19  4012.8 1731.94  4373.1 1729.69
  4378.2 1731.53  4437.0 1731.34  4457.4 1729.60  4672.0 1730.86  4787.5 1729.32
  4809.8 1727.70  4893.4 1729.30  4965.5 1728.60  4982.5 1728.74  4988.8 1727.12
  4989.7 1719.88  4990.2 1719.38  5010.3 1719.88  5027.1 1720.17  5043.8 1728.16
  5106.6 1728.83  5218.0 1730.49  5298.8 1729.86  5338.7 1730.51  5567.1 1730.65
  6190.5 1732.04  6221.0 1732.02  6999.9 1741.71  7129.6 1743.95  7234.2 1744.84
#Mann=16,-1,0
  3219.1   0.035       0  3301.0   0.063       0  3798.1   0.094       0
  4012.8   0.063       0  4965.5   0.035       0  4989.7   0.035       0
  5010.3   0.035       0  5106.6   0.063       0  5218.0   0.094       0
  5298.8   0.063       0  5338.7   0.094       0  5567.1   0.063       0
  6190.5   0.094       0  6221.0   0.063       0  6999.9   0.094       0
  7129.6   0.063       0
Bank Sta=4989.7,5010.3
Exp/Cntr=0.3,0.1

Type RM Length L Ch R = 1,23184,700,700,700
BEGIN DESCRIPTION:
Cat Claw Creek 17.0
END DESCRIPTION:
XS GIS Cut Line= 3
      1578996.17      6845928.61      1579651.79      6845505.20
      1581191.72      6844578.74
#Sta/Elev= 30
  4349.0 1731.28  4609.5 1730.67  4658.7 1730.31  4689.0 1728.12  4806.0 1728.34
  4927.9 1728.21  4954.9 1724.42  4970.1 1719.97  4985.3 1722.07  4989.7 1719.97
  4990.2 1719.47  5010.4 1719.97  5014.2 1722.93  5049.9 1723.14  5073.0 1727.10
  5085.8 1727.73  5094.1 1726.73  5252.9 1729.63  5284.0 1728.36  5341.2 1729.03
  5544.3 1730.73  5693.7 1728.78  5701.2 1728.44  5811.2 1728.90  5883.0 1729.38
  5946.4 1730.67  6108.3 1730.24  6222.2 1730.05  6534.9 1733.19  6926.6 1740.51
#Mann=11,-1,0
  4349.0   0.063       0  4806.0   0.035       0  4989.7   0.035       0
  5010.4   0.035       0  5085.8   0.063       0  5341.2   0.035       0
  5693.7   0.063       0  5701.2   0.094       0  5811.2   0.063       0
  5883.0   0.035       0  6108.3   0.063       0
Bank Sta=4989.7,5010.4
Exp/Cntr=0.3,0.1