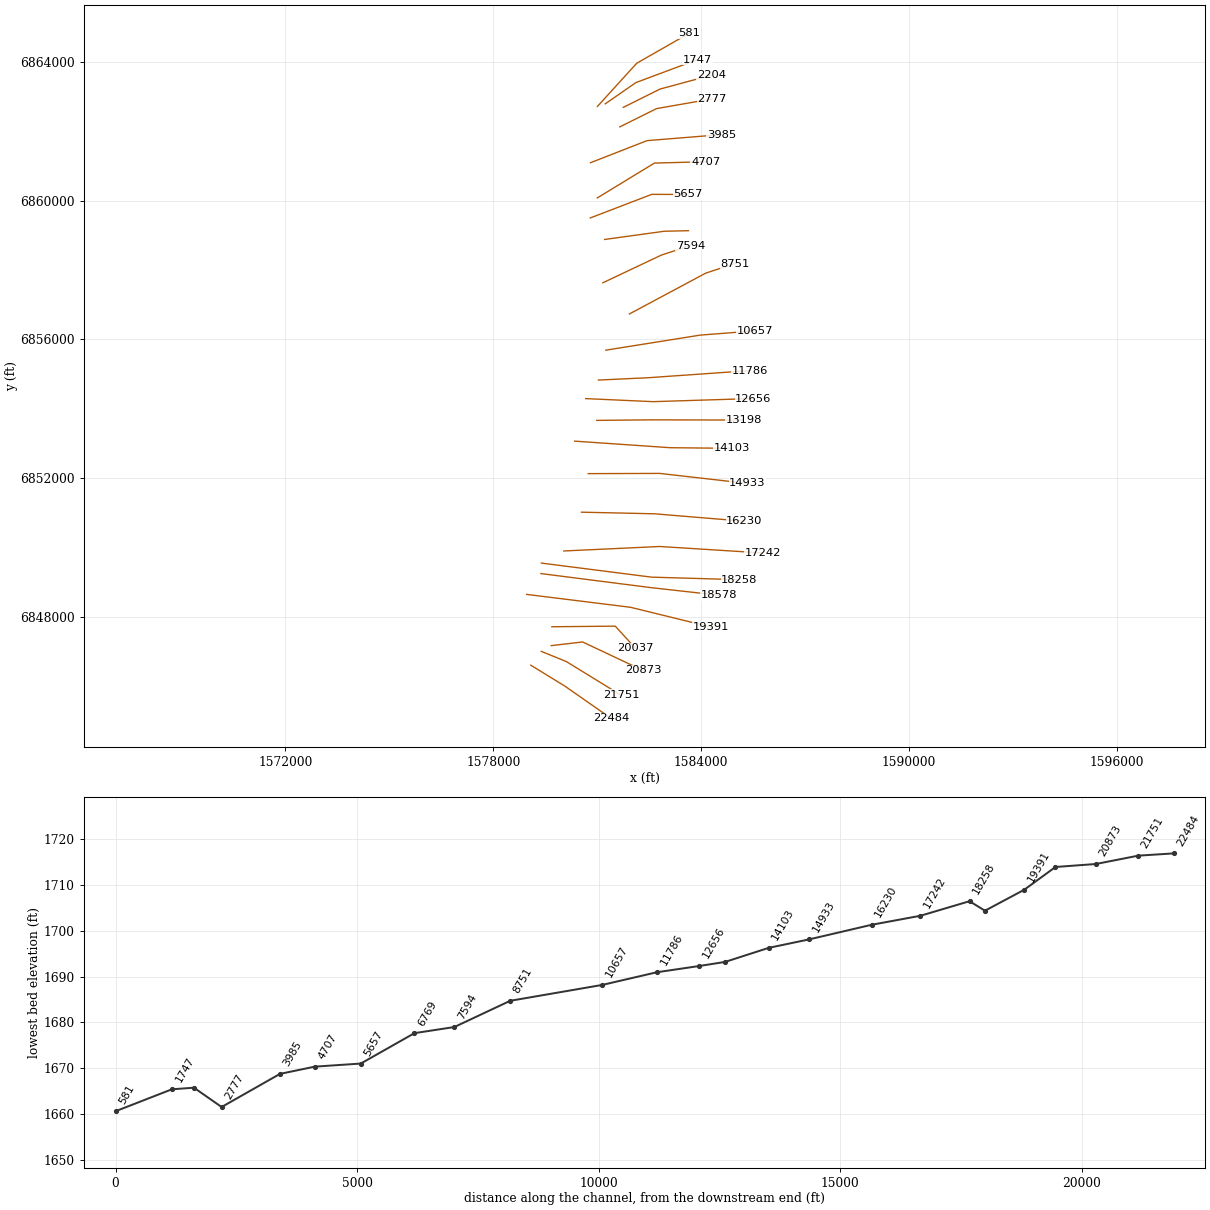
HEC-RAS study Cat Claw Creek.prj: Cat Claw Creek Base Level Engineering

--- Cat Claw Creek.g01 (geometry) --- (continued)

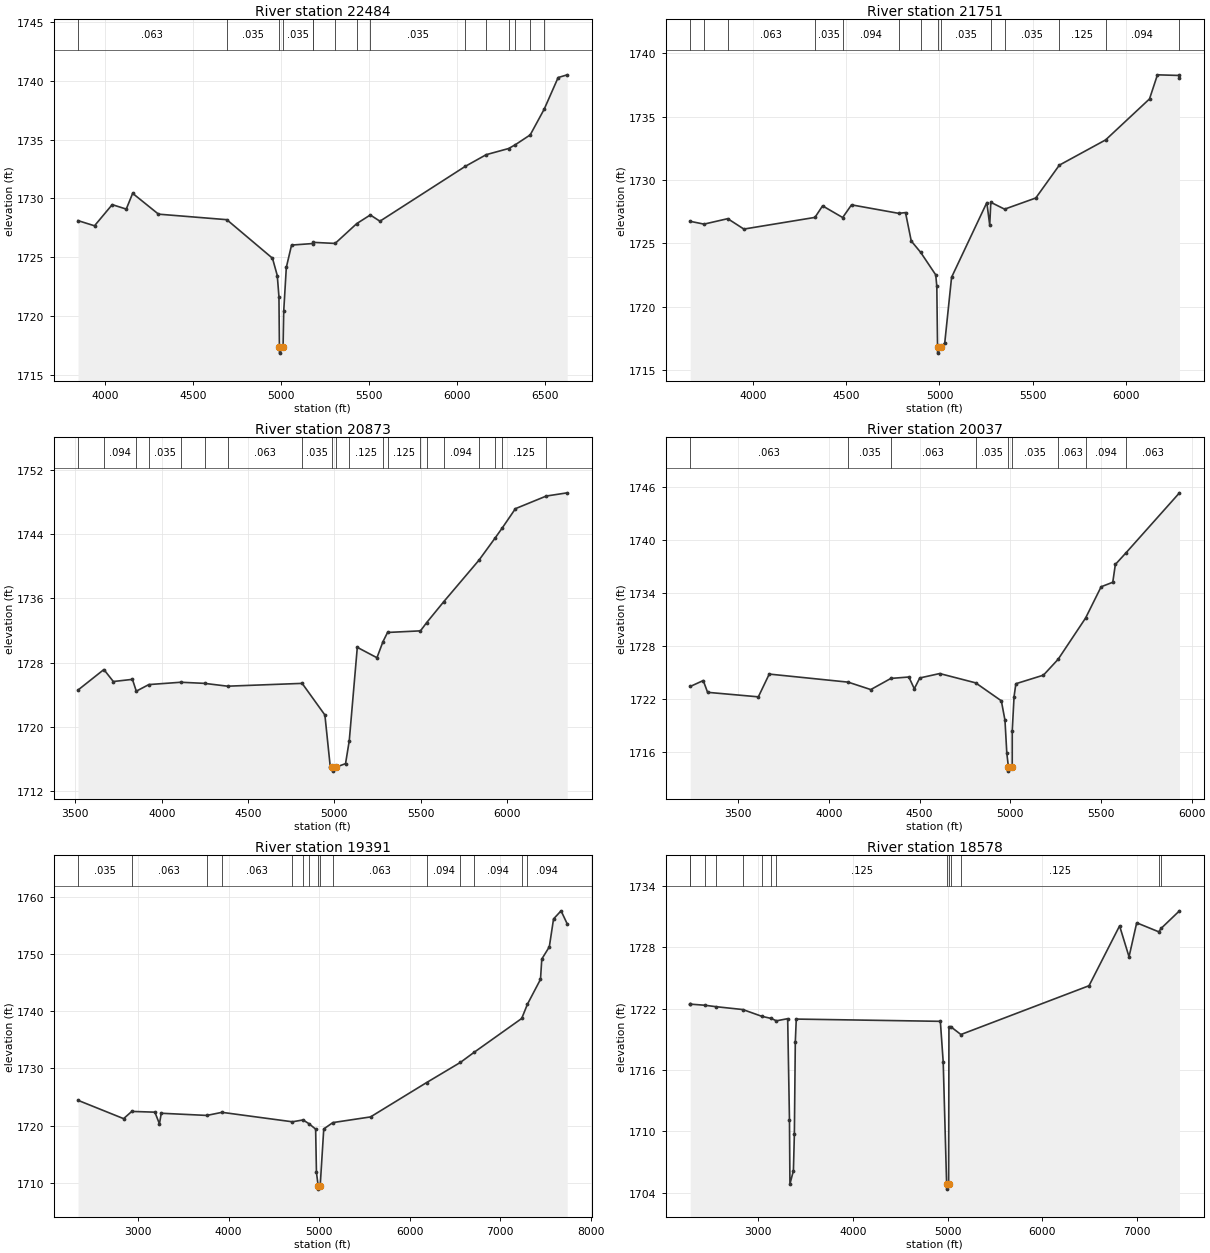
Type RM Length L Ch R = 1,22484,733,733,733
BEGIN DESCRIPTION:
Cat Claw Creek 16.0
END DESCRIPTION:
XS GIS Cut Line= 3
      1579081.37      6846602.84      1580065.23      6845998.78
      1581397.43      6845068.78
#Sta/Elev= 30
  3845.5 1728.11  3939.3 1727.67  4039.8 1729.47  4119.6 1729.09  4155.9 1730.43
  4302.7 1728.66  4690.7 1728.19  4950.3 1724.91  4977.5 1723.44  4987.0 1721.64
  4989.7 1717.34  4990.2 1716.84  5010.4 1717.34  5014.1 1720.40  5028.9 1724.13
  5058.6 1726.03  5178.7 1726.16  5183.0 1726.26  5306.1 1726.17  5429.2 1727.86
  5505.9 1728.59  5560.7 1728.06  6044.9 1732.72  6164.5 1733.72  6291.2 1734.24
  6329.2 1734.56  6414.3 1735.40  6493.8 1737.59  6573.0 1740.28  6624.7 1740.51
#Mann=15,-1,0
  3845.5   0.063       0  4690.7   0.035       0  4989.7   0.035       0
  5010.4   0.035       0  5178.7   0.094       0  5183.0   0.125       0
  5306.1   0.094       0  5429.2   0.063       0  5505.9   0.035       0
  6044.9   0.094       0  6164.5   0.125       0  6291.2   0.094       0
  6329.2   0.125       0  6414.3   0.063       0  6493.8   0.125       0
Bank Sta=4989.7,5010.4
Exp/Cntr=0.3,0.1

Type RM Length L Ch R = 1,21751,878,878,878
BEGIN DESCRIPTION:
Cat Claw Creek 15.5
END DESCRIPTION:
XS GIS Cut Line= 3
      1579383.45      6847001.78      1580106.67      6846707.42
      1581680.42      6845740.86
#Sta/Elev= 30
  3661.2 1726.74  3735.3 1726.52  3862.6 1726.95  3949.4 1726.13  4331.0 1727.05
  4372.1 1727.96  4480.0 1727.04  4527.5 1728.04  4780.9 1727.37  4817.5 1727.43
  4848.3 1725.19  4899.1 1724.29  4979.8 1722.52  4985.6 1721.62  4989.5 1716.85
  4990.0 1716.35  5010.6 1716.85  5028.2 1717.15  5064.9 1722.33  5254.3 1728.22
  5269.8 1726.44  5275.6 1728.24  5349.7 1727.70  5517.2 1728.58  5643.7 1731.17
  5892.3 1733.16  6128.0 1736.39  6170.6 1738.29  6287.2 1738.24  6288.9 1738.06
#Mann=14,-1,0
  3661.2   0.063       0  3735.3   0.035       0  3862.6   0.063       0
  4331.0   0.035       0  4480.0   0.094       0  4780.9   0.063       0
  4899.1   0.035       0  4989.5   0.035       0  5010.6   0.035       0
  5275.6   0.063       0  5349.7   0.035       0  5643.7   0.125       0
  5892.3   0.094       0  6287.2   0.063       0
Bank Sta=4989.5,5010.6
Exp/Cntr=0.3,0.1

Type RM Length L Ch R = 1,20873,836,836,836
BEGIN DESCRIPTION:
Cat Claw Creek 15.0
END DESCRIPTION:
XS GIS Cut Line= 3
      1579671.69      6847167.13      1580575.93      6847273.17
      1582317.23      6846452.81
#Sta/Elev= 30
  3515.0 1724.61  3665.0 1727.16  3719.7 1725.67  3830.5 1725.94  3852.8 1724.47
  3925.4 1725.29  4110.9 1725.58  4248.4 1725.44  4381.9 1725.09  4814.0 1725.44
  4945.8 1721.51  4977.1 1715.03  4989.4 1715.03  4989.9 1714.53  5010.6 1715.03
  5065.5 1715.46  5087.1 1718.32  5133.6 1729.92  5247.5 1728.63  5282.5 1730.63
  5308.9 1731.77  5499.7 1731.97  5535.8 1733.00  5634.8 1735.60  5839.2 1740.77
  5934.2 1743.57  5974.2 1744.78  6049.9 1747.16  6228.8 1748.73  6350.3 1749.13
#Mann=20,-1,0
  3515.0   0.063       0  3665.0   0.094       0  3852.8   0.063       0
  3925.4   0.035       0  4110.9   0.063       0  4248.4   0.094       0
  4381.9   0.063       0  4814.0   0.035       0  4989.4   0.035       0
  5010.6   0.035       0  5087.1   0.125       0  5282.5   0.094       0
  5308.9   0.125       0  5499.7   0.094       0  5535.8   0.063       0
  5634.8   0.094       0  5839.2   0.125       0  5934.2   0.094       0
  5974.2   0.125       0  6228.8   0.063       0
Bank Sta=4989.4,5010.6
Exp/Cntr=0.3,0.1

Type RM Length L Ch R = 1,20037,646,646,646
BEGIN DESCRIPTION:
Cat Claw Creek 14.0
END DESCRIPTION:
XS GIS Cut Line= 3
      1579689.33      6847712.32      1581517.33      6847729.39
      1582105.00      6847087.99
#Sta/Elev= 30
  3234.9 1723.44  3306.7 1724.11  3330.6 1722.78  3610.6 1722.27  3670.6 1724.84
  4105.7 1723.93  4230.6 1723.09  4341.5 1724.35  4440.6 1724.51  4470.6 1723.18
  4500.6 1724.40  4610.6 1724.90  4808.8 1723.85  4950.6 1721.82  4970.6 1719.63
  4980.7 1715.93  4989.4 1714.38  4989.9 1713.88  5010.6 1714.38  5010.7 1718.43
  5020.7 1722.29  5030.7 1723.75  5182.8 1724.72  5263.7 1726.51  5414.9 1731.16
  5500.9 1734.70  5565.1 1735.21  5579.3 1737.22  5638.3 1738.54  5932.9 1745.31
#Mann=9,-1,0
  3234.9   0.063       0  4105.7   0.035       0  4341.5   0.063       0
  4808.8   0.035       0  4989.4   0.035       0  5010.6   0.035       0
  5263.7   0.063       0  5414.9   0.094       0  5638.3   0.063       0
Bank Sta=4989.4,5010.6
Exp/Cntr=0.3,0.1

Type RM Length L Ch R = 1,19391,813,813,813
BEGIN DESCRIPTION:
Cat Claw Creek 13.0
END DESCRIPTION:
XS GIS Cut Line= 3
      1578962.80      6848645.19      1581958.76      6848273.85
      1584271.71      6847705.69
#Sta/Elev= 30
  2337.6 1724.43  2840.9 1721.23  2931.2 1722.49  3186.2 1722.36  3236.6 1720.32
  3256.8 1722.17  3759.9 1721.79  3926.5 1722.33  4704.1 1720.68  4821.5 1721.00
  4887.8 1720.34  4960.8 1719.40  4969.8 1711.83  4989.4 1709.42  4989.9 1708.92
  5010.7 1709.42  5050.4 1719.43  5151.1 1720.54  5566.7 1721.53  6185.8 1727.53
  6558.9 1731.05  6710.8 1732.82  7235.5 1738.72  7299.0 1741.22  7443.0 1745.56
  7457.2 1749.10  7540.3 1751.23  7587.1 1756.11  7670.1 1757.52  7738.2 1755.23
#Mann=15,-1,0
  2337.6   0.035       0  2931.2   0.063       0  3759.9   0.094       0
  3926.5   0.063       0  4704.1   0.035       0  4821.5   0.063       0
  4887.8   0.035       0  4989.4   0.035       0  5010.7   0.035       0
  5151.1   0.063       0  6185.8   0.094       0  6558.9   0.125       0
  6710.8   0.094       0  7235.5   0.063       0  7299.0   0.094       0
Bank Sta=4989.4,5010.7
Exp/Cntr=0.3,0.1

Type RM Length L Ch R = 1,18578,320,320,320
BEGIN DESCRIPTION:
Cat Claw Creek 12.9
END DESCRIPTION:
XS GIS Cut Line= 3
      1579373.70      6849246.25      1582552.76      6848840.30
      1584504.55      6848622.33
#Sta/Elev= 30
  2280.6 1722.43  2283.3 1722.43  2436.1 1722.32  2554.1 1722.18  2836.7 1721.90
  3037.0 1721.24  3137.2 1721.03  3191.6 1720.80  3310.2 1721.01  3329.0 1711.15
  3334.0 1704.85  3370.7 1706.15  3380.8 1709.70  3390.8 1718.73  3400.9 1720.97
  4923.2 1720.75  4953.4 1716.75  4989.4 1704.85  4989.9 1704.35  5010.7 1704.85
  5013.9 1720.16  5031.0 1720.24  5140.3 1719.46  6493.9 1724.23  6816.8 1730.08
  6916.6 1727.06  6997.5 1730.38  7230.4 1729.50  7257.4 1729.85  7449.4 1731.55
#Mann=14,-1,0
  2280.6   0.125       0  2283.3   0.094       0  2436.1   0.063       0
  2554.1   0.125       0  2836.7   0.094       0  3037.0   0.063       0
  3137.2   0.094       0  3191.6   0.125       0  4989.4    0.07       0
  5010.7   0.125       0  5031.0   0.094       0  5140.3   0.125       0
  7230.4   0.094       0  7257.4   0.125       0
Bank Sta=4989.4,5010.7
Exp/Cntr=0.3,0.1

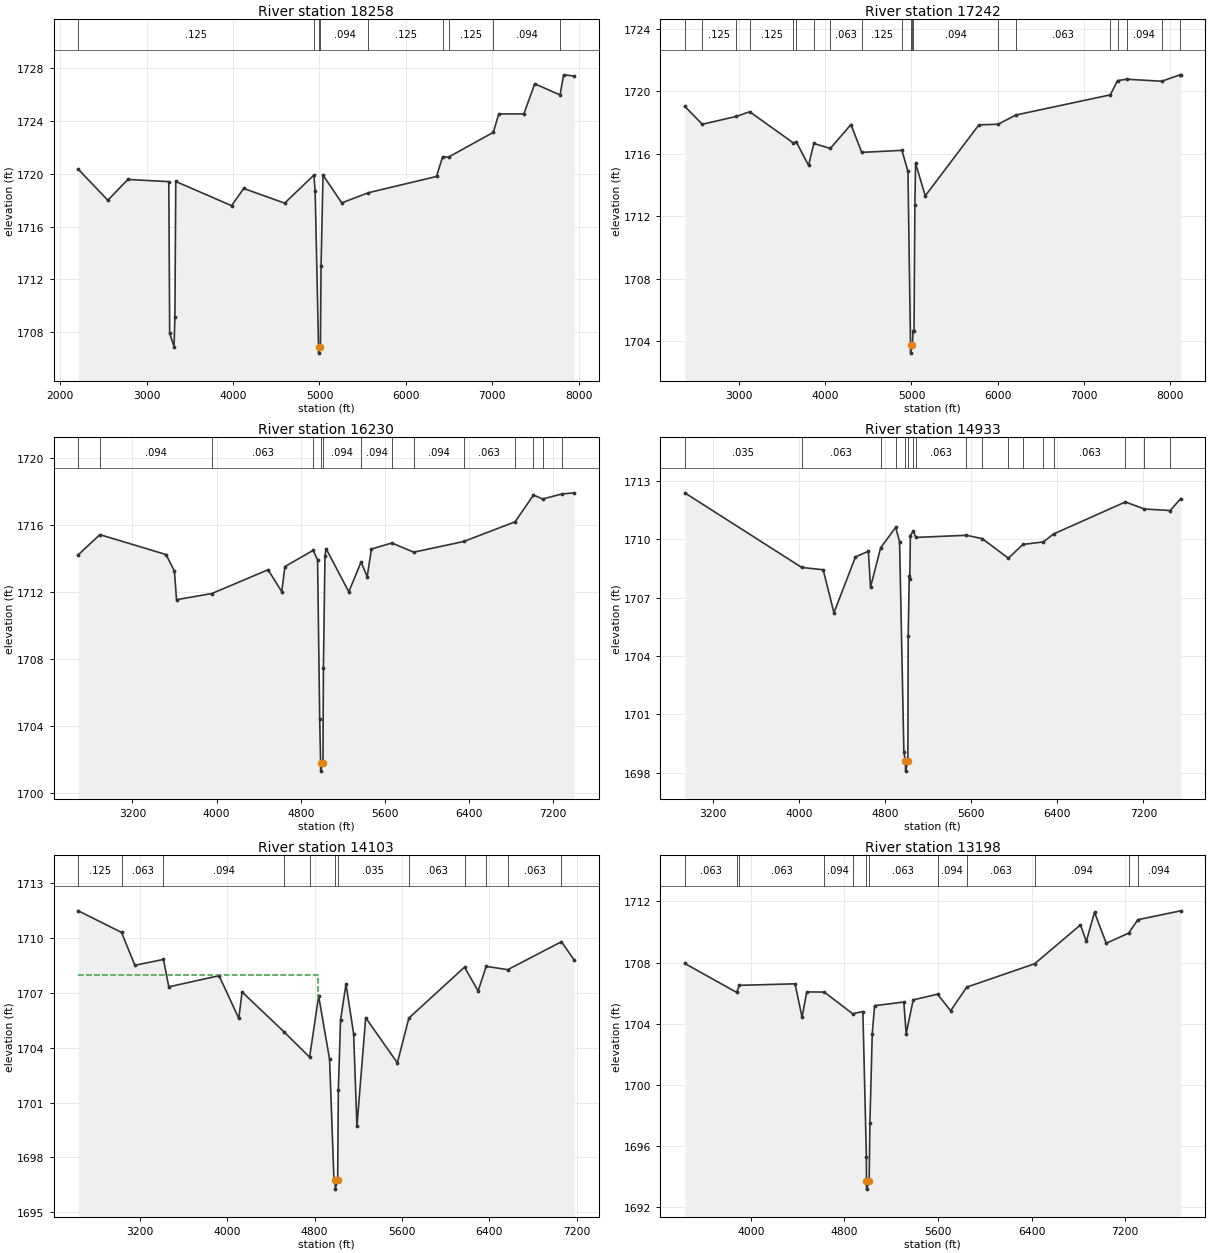
Type RM Length L Ch R = 1,18258,1016,1016,1016
BEGIN DESCRIPTION:
Cat Claw Creek 12.8
END DESCRIPTION:
XS GIS Cut Line= 3
      1579386.54      6849549.09      1582565.54      6849143.15
      1585097.07      6849069.81
#Sta/Elev= 30
  2209.6 1720.33  2550.8 1717.99  2782.7 1719.56  3256.5 1719.40  3266.6 1707.91
  3317.0 1706.92  3327.1 1709.12  3337.1 1719.41  3982.3 1717.58  4123.5 1718.88
  4597.3 1717.77  4935.5 1719.89  4950.1 1718.66  4989.0 1706.92  4989.5 1706.42
  5011.1 1706.92  5018.3 1713.00  5040.9 1719.89  5257.7 1717.79  5567.1 1718.56
  6354.3 1719.79  6423.9 1721.26  6494.6 1721.26  7011.7 1723.13  7074.6 1724.52
  7364.7 1724.52  7490.7 1726.80  7784.0 1725.96  7824.9 1727.48  7947.0 1727.39
#Mann=9,-1,0
  2209.6   0.125       0  4935.5   0.094       0  4989.0    0.07       0
  5011.1   0.094       0  5567.1   0.125       0  6423.9   0.094       0
  6494.6   0.125       0  7011.7   0.094       0  7784.0   0.125       0
Bank Sta=4989,5011.1
Exp/Cntr=0.3,0.1

Type RM Length L Ch R = 1,17242,1012,1012,1012
BEGIN DESCRIPTION:
Cat Claw Creek 12.6
END DESCRIPTION:
XS GIS Cut Line= 3
      1580032.96      6849898.45      1582805.46      6850027.65
      1585766.88      6849841.03
#Sta/Elev= 30
  2374.8 1719.03  2577.6 1717.89  2971.9 1718.39  3126.3 1718.69  3632.6 1716.69
  3665.1 1716.77  3808.4 1715.26  3869.3 1716.66  4060.0 1716.34  4298.9 1717.87
  4424.4 1716.09  4889.8 1716.22  4959.6 1714.87  4989.0 1703.75  4989.5 1703.25
  5011.1 1703.75  5018.2 1704.69  5029.7 1704.65  5039.7 1712.74  5047.6 1715.40
  5159.9 1713.31  5781.1 1717.85  6003.4 1717.89  6210.1 1718.48  7303.2 1719.77
  7386.8 1720.68  7493.4 1720.77  7899.4 1720.64  8109.0 1721.05  8117.6 1721.02
#Mann=20,-1,0
  2374.8   0.094       0  2577.6   0.125       0  2971.9   0.094       0
  3126.3   0.125       0  3632.6   0.094       0  3665.1   0.063       0
  3869.3   0.094       0  4060.0   0.063       0  4424.4   0.125       0
  4889.8   0.063       0  4989.0   0.063       0  5011.1   0.063       0
  5018.2   0.094       0  6003.4   0.035       0  6210.1   0.063       0
  7303.2   0.094       0  7386.8   0.063       0  7493.4   0.094       0
  7899.4   0.125       0  8109.0   0.063       0
Bank Sta=4989,5011.1
Exp/Cntr=0.3,0.1

Type RM Length L Ch R = 1,16230,1297,1297,1297
BEGIN DESCRIPTION:
Cat Claw Creek 12.3
END DESCRIPTION:
XS GIS Cut Line= 3
      1580541.83      6851017.78      1582650.42      6850971.22
      1585245.52      6850756.19
#Sta/Elev= 30
  2685.9 1714.22  2891.0 1715.42  3519.3 1714.23  3599.3 1713.24  3619.3 1711.53
  3955.9 1711.90  4489.5 1713.32  4619.5 1712.01  4649.5 1713.51  4917.7 1714.48
  4960.1 1713.91  4980.2 1704.40  4988.9 1701.78  4989.4 1701.28  5011.1 1701.78
  5015.5 1707.47  5030.4 1714.12  5040.4 1714.59  5257.0 1712.00  5373.2 1713.78
  5431.8 1712.91  5471.9 1714.56  5666.4 1714.92  5874.1 1714.37  6348.9 1715.01
  6838.1 1716.19  7012.4 1717.79  7099.3 1717.55  7280.7 1717.85  7399.0 1717.92
#Mann=14,-1,0
  2685.9   0.125       0  2891.0   0.094       0  3955.9   0.063       0
  4917.7   0.094       0  4988.9   0.063       0  5011.1   0.094       0
  5373.2   0.094       0  5666.4   0.063       0  5874.1   0.094       0
  6348.9   0.063       0  6838.1   0.094       0  7012.4   0.063       0
  7099.3   0.094       0  7280.7   0.125       0
Bank Sta=4988.9,5011.1
Exp/Cntr=0.3,0.1

Type RM Length L Ch R = 1,14933,830,830,830
BEGIN DESCRIPTION:
Cat Claw Creek 12.0
END DESCRIPTION:
XS GIS Cut Line= 3
      1580738.66      6852130.02      1582800.75      6852136.26
      1585330.91      6851848.23
#Sta/Elev= 30
  2937.9 1712.38  4024.3 1708.55  4224.2 1708.43  4324.2 1706.22  4524.2 1709.09
  4644.2 1709.38  4664.2 1707.54  4758.3 1709.56  4898.4 1710.61  4934.3 1709.86
  4974.3 1699.07  4988.9 1698.59  4989.4 1698.09  5011.2 1698.59  5014.3 1705.02
  5024.1 1708.13  5029.2 1707.98  5034.5 1710.18  5061.2 1710.42  5085.4 1710.09
  5554.3 1710.20  5702.3 1710.03  5945.7 1709.02  6080.0 1709.73  6270.6 1709.86
  6366.4 1710.27  7032.7 1711.91  7210.7 1711.55  7449.4 1711.47  7546.5 1712.08
#Mann=17,-1,0
  2937.9   0.035       0  4024.3   0.063       0  4758.3   0.094       0
  4898.4   0.063       0  4988.9   0.063       0  5011.2   0.063       0
  5061.2   0.035       0  5085.4   0.063       0  5554.3   0.035       0
  5702.3   0.063       0  5945.7   0.035       0  6080.0   0.063       0
  6270.6   0.035       0  6366.4   0.063       0  7032.7   0.094       0
  7210.7   0.063       0  7449.4   0.094       0
Bank Sta=4988.9,5011.2
Exp/Cntr=0.3,0.1

Type RM Length L Ch R = 1,14103,905,905,905
BEGIN DESCRIPTION:
Cat Claw Creek 11.0
END DESCRIPTION:
XS GIS Cut Line= 3
      1580348.03      6853067.50      1583097.73      6852878.18
      1584885.03      6852859.80
#Sta/Elev= 30
  2634.9 1711.49  3030.5 1710.31  3153.1 1708.51  3415.2 1708.83  3463.8 1707.33
  3924.9 1707.94  4105.3 1705.60  4135.4 1707.05  4517.6 1704.88  4754.3 1703.48
  4837.1 1706.83  4937.3 1703.37  4977.4 1696.76  4988.7 1696.76  4989.2 1696.26
  5011.3 1696.76  5017.5 1701.67  5037.5 1705.50  5087.7 1707.48  5157.8 1704.76
  5187.9 1699.70  5268.1 1705.64  5558.4 1703.17  5663.8 1705.62  6174.1 1708.41
  6298.4 1707.10  6372.2 1708.45  6570.3 1708.27  7062.1 1709.80  7178.5 1708.80
#Mann=12,-1,0
  2634.9   0.125       0  3030.5   0.063       0  3415.2   0.094       0
  4517.6   0.063       0  4754.3   0.035       0  4988.7   0.035       0
  5011.3   0.035       0  5663.8   0.063       0  6174.1   0.094       0
  6372.2   0.035       0  6570.3   0.063       0  7062.1   0.094       0
#XS Ineff=2,0
    0.00 4827.00 1708.00               0
Permanent Ineff=
       F       F
Bank Sta=4988.7,5011.3
Exp/Cntr=0.3,0.1

Type RM Length L Ch R = 1,13198,542,542,542
BEGIN DESCRIPTION:
Cat Claw Creek 10.0
END DESCRIPTION:
XS GIS Cut Line= 3
      1580982.74      6853666.06      1582546.86      6853681.94
      1585221.05      6853675.57
#Sta/Elev= 30
  3435.8 1707.94  3878.6 1706.05  3901.3 1706.51  4378.1 1706.61  4438.1 1704.42
  4478.1 1706.08  4628.3 1706.07  4869.4 1704.66  4958.1 1704.79  4988.1 1695.29
  4988.6 1693.69  4989.1 1693.19  5011.5 1693.69  5018.1 1697.51  5038.1 1703.34
  5058.1 1705.18  5308.1 1705.42  5328.1 1703.35  5388.1 1705.56  5596.0 1705.93
  5708.1 1704.85  5845.5 1706.39  6426.1 1707.92  6818.1 1710.46  6868.1 1709.38
  6938.1 1711.29  7038.1 1709.26  7229.5 1709.92  7308.9 1710.80  7674.2 1711.38
#Mann=12,-1,0
  3435.8   0.063       0  3878.6   0.035       0  3901.3   0.063       0
  4628.3   0.094       0  4869.4   0.063       0  4988.6   0.063       0
  5011.5   0.063       0  5596.0   0.094       0  5845.5   0.063       0
  6426.1   0.094       0  7229.5   0.063       0  7308.9   0.094       0
Bank Sta=4988.6,5011.5
Exp/Cntr=0.3,0.1

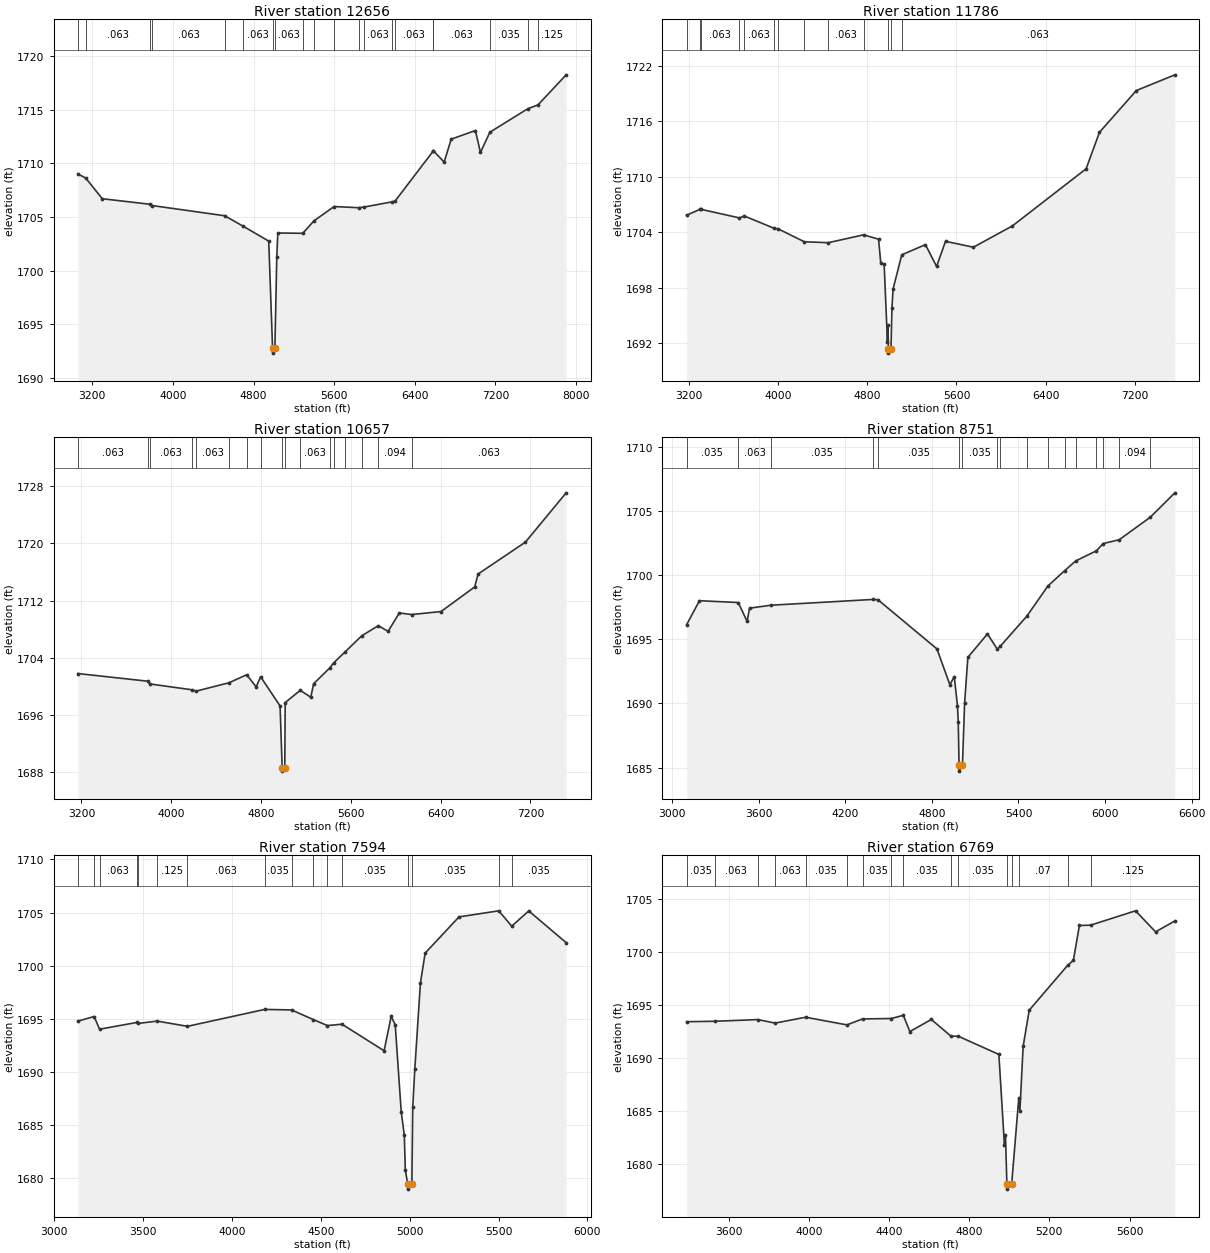
Type RM Length L Ch R = 1,12656,870,870,870
BEGIN DESCRIPTION:
Cat Claw Creek 9.0
END DESCRIPTION:
XS GIS Cut Line= 3
      1580663.63      6854294.91      1582604.51      6854206.44
      1585505.19      6854297.25
#Sta/Elev= 30
  3057.1 1709.02  3134.1 1708.64  3298.7 1706.71  3773.3 1706.19  3794.7 1706.07
  4513.2 1705.12  4691.4 1704.17  4950.4 1702.75  4988.4 1692.79  4988.9 1692.29
  5011.6 1692.79  5030.5 1701.29  5040.5 1703.51  5288.3 1703.48  5398.8 1704.64
  5599.5 1705.98  5842.5 1705.87  5900.6 1705.94  6170.3 1706.41  6202.8 1706.47
  6579.6 1711.12  6583.2 1711.20  6691.3 1710.13  6761.4 1712.27  7001.5 1713.08
  7051.5 1711.03  7145.0 1712.92  7518.8 1715.10  7623.8 1715.48  7902.1 1718.28
#Mann=20,-1,0
  3057.1   0.125       0  3134.1   0.063       0  3773.3   0.035       0
  3794.7   0.063       0  4513.2   0.035       0  4691.4   0.063       0
  4988.4   0.063       0  5011.6   0.063       0  5288.3   0.063       0
  5398.8   0.035       0  5599.5   0.063       0  5842.5   0.035       0
  5900.6   0.063       0  6170.3   0.035       0  6202.8   0.063       0
  6579.6   0.035       0  6583.2   0.063       0  7145.0   0.035       0
  7518.8   0.063       0  7623.8   0.125       0
Bank Sta=4988.4,5011.6
Exp/Cntr=0.3,0.1

Type RM Length L Ch R = 1,11786,1129,1129,1129
BEGIN DESCRIPTION:
Cat Claw Creek 8.0
END DESCRIPTION:
XS GIS Cut Line= 3
      1581032.95      6854829.91      1582473.66      6854897.39
      1585410.28      6855102.99
#Sta/Elev= 30
  3175.8 1705.85  3295.7 1706.49  3300.6 1706.50  3650.5 1705.56  3693.6 1705.77
  3965.0 1704.42  3995.5 1704.39  4233.1 1702.98  4448.7 1702.88  4764.8 1703.73
  4900.1 1703.26  4920.2 1700.64  4950.2 1700.54  4980.0 1692.19  4985.1 1693.95
  4988.4 1691.44  4988.9 1690.94  5011.7 1691.44  5020.4 1695.86  5030.4 1697.87
  5108.6 1701.57  5321.1 1702.67  5421.4 1700.31  5501.6 1703.03  5752.2 1702.39
  6103.1 1704.70  6764.7 1710.87  6885.0 1714.82  7215.8 1719.33  7561.9 1721.03
#Mann=13,-1,0
  3175.8   0.063       0  3295.7   0.035       0  3300.6   0.063       0
  3650.5   0.035       0  3693.6   0.063       0  3965.0   0.035       0
  3995.5   0.063       0  4233.1   0.035       0  4448.7   0.063       0
  4764.8   0.035       0  4988.4   0.035       0  5011.7   0.035       0
  5108.6   0.063       0
Bank Sta=4988.4,5011.7
Exp/Cntr=0.3,0.1

Type RM Length L Ch R = 1,10657,1906,1906,1906
BEGIN DESCRIPTION:
Cat Claw Creek 7.5
END DESCRIPTION:
XS GIS Cut Line= 3
      1581246.52      6855692.14      1583972.04      6856126.88
      1585557.28      6856248.81
#Sta/Elev= 30
  3168.8 1701.81  3789.9 1700.74  3807.5 1700.36  4185.0 1699.54  4221.3 1699.35
  4514.2 1700.52  4672.5 1701.64  4756.7 1699.94  4796.3 1701.36  4969.8 1697.28
  4988.3 1688.68  4988.8 1688.18  5011.8 1688.68  5015.3 1697.75  5149.4 1699.47
  5243.2 1698.50  5268.9 1700.39  5412.5 1702.59  5448.1 1703.31  5549.6 1704.84
  5696.4 1707.07  5844.6 1708.49  5932.8 1707.71  6032.0 1710.27  6142.4 1710.05
  6404.0 1710.47  6704.0 1713.91  6734.1 1715.71  7155.3 1720.16  7518.7 1727.05
#Mann=17,-1,0
  3168.8   0.063       0  3789.9   0.035       0  3807.5   0.063       0
  4185.0   0.035       0  4221.3   0.063       0  4514.2   0.035       0
  4672.5   0.063       0  4796.3   0.035       0  4988.3   0.035       0
  5011.8   0.035       0  5149.4   0.063       0  5412.5   0.035       0
  5448.1   0.063       0  5549.6   0.094       0  5696.4   0.063       0
  5844.6   0.094       0  6142.4   0.063       0
Bank Sta=4988.3,5011.8
Exp/Cntr=0.3,0.1

Type RM Length L Ch R = 1,8751,1157,1157,1157
BEGIN DESCRIPTION:
Cat Claw Creek 7.0
END DESCRIPTION:
XS GIS Cut Line= 3
      1581926.71      6856737.15      1584129.70      6857915.49
      1584970.36      6858190.72
#Sta/Elev= 30
  3100.6 1696.15  3189.4 1698.02  3458.1 1697.88  3519.9 1696.40  3536.2 1697.44
  3686.5 1697.67  4394.5 1698.12  4426.8 1698.09  4834.9 1694.26  4924.5 1691.47
  4955.2 1692.09  4977.2 1689.82  4982.8 1688.59  4988.2 1685.22  4988.7 1684.72
  5011.9 1685.22  5026.7 1690.02  5049.3 1693.60  5185.2 1695.43  5253.7 1694.23
  5273.5 1694.46  5457.0 1696.80  5604.9 1699.18  5719.4 1700.36  5796.1 1701.12
  5940.6 1701.92  5986.5 1702.48  6098.0 1702.78  6313.0 1704.53  6483.5 1706.44
#Mann=17,-1,0
  3100.6   0.035       0  3458.1   0.063       0  3686.5   0.035       0
  4394.5   0.063       0  4426.8   0.035       0  4988.2   0.035       0
  5011.9   0.035       0  5253.7   0.063       0  5273.5   0.094       0
  5457.0   0.063       0  5604.9   0.094       0  5719.4   0.035       0
  5796.1   0.063       0  5940.6   0.094       0  5986.5   0.063       0
  6098.0   0.094       0  6313.0   0.063       0
Bank Sta=4988.2,5011.9
Exp/Cntr=0.3,0.1

Type RM Length L Ch R = 1,7594,825,825,825
BEGIN DESCRIPTION:
Cat Claw Creek 6.0
END DESCRIPTION:
XS GIS Cut Line= 3
      1581160.86      6857636.78      1582848.95      6858435.46
      1583684.94      6858711.23
#Sta/Elev= 30
  3132.5 1694.80  3223.6 1695.23  3254.1 1694.04  3466.4 1694.68  3470.3 1694.58
  3578.4 1694.80  3748.9 1694.31  4183.7 1695.90  4335.0 1695.85  4456.3 1694.95
  4536.8 1694.38  4618.6 1694.51  4855.6 1692.01  4895.6 1695.25  4918.2 1694.46
  4952.2 1686.24  4969.4 1684.07  4974.9 1680.84  4988.1 1679.50  4988.6 1679.00
  5011.9 1679.50  5016.9 1686.70  5028.4 1690.26  5060.1 1698.38  5086.6 1701.19
  5277.2 1704.60  5500.8 1705.17  5574.1 1703.73  5669.8 1705.16  5880.3 1702.18
#Mann=16,-1,0
  3132.5   0.063       0  3223.6   0.094       0  3254.1   0.063       0
  3466.4   0.125       0  3470.3   0.063       0  3578.4   0.125       0
  3748.9   0.063       0  4183.7   0.035       0  4335.0   0.063       0
  4456.3   0.035       0  4536.8   0.094       0  4618.6   0.035       0
  4988.1   0.035       0  5011.9   0.035       0  5500.8   0.063       0
  5574.1   0.035       0
Bank Sta=4988.1,5011.9
Exp/Cntr=0.3,0.1

Type RM Length L Ch R = 1,6769,1112,1112,1112
BEGIN DESCRIPTION:
Cat Claw Creek 5.0
END DESCRIPTION:
XS GIS Cut Line= 3
      1581212.09      6858886.25      1582927.73      6859122.65
      1583630.96      6859139.93
#Sta/Elev= 30
  3390.6 1693.42  3530.5 1693.46  3745.6 1693.62  3832.2 1693.29  3984.3 1693.84
  4190.0 1693.12  4267.9 1693.68  4411.4 1693.72  4471.7 1694.02  4503.9 1692.49
  4611.1 1693.63  4709.3 1692.06  4746.4 1692.05  4948.1 1690.34  4975.9 1681.79
  4981.0 1682.72  4988.1 1678.17  4988.6 1677.67  5012.0 1678.17  5047.6 1686.28
  5052.9 1685.01  5069.2 1691.10  5099.5 1694.50  5291.1 1698.72  5319.8 1699.19
  5349.8 1702.47  5405.3 1702.50  5629.9 1703.85  5729.9 1701.87  5825.9 1702.90
#Mann=16,-1,0
  3390.6   0.035       0  3530.5   0.063       0  3745.6   0.035       0
  3832.2   0.063       0  3984.3   0.035       0  4190.0   0.063       0
  4267.9   0.035       0  4411.4   0.063       0  4471.7   0.035       0
  4709.3    0.07       0  4746.4   0.035       0  4988.1   0.035       0
  5012.0   0.035       0  5047.6    0.07       0  5291.1   0.094       0
  5405.3   0.125       0
Bank Sta=4988.1,5012
Exp/Cntr=0.3,0.1

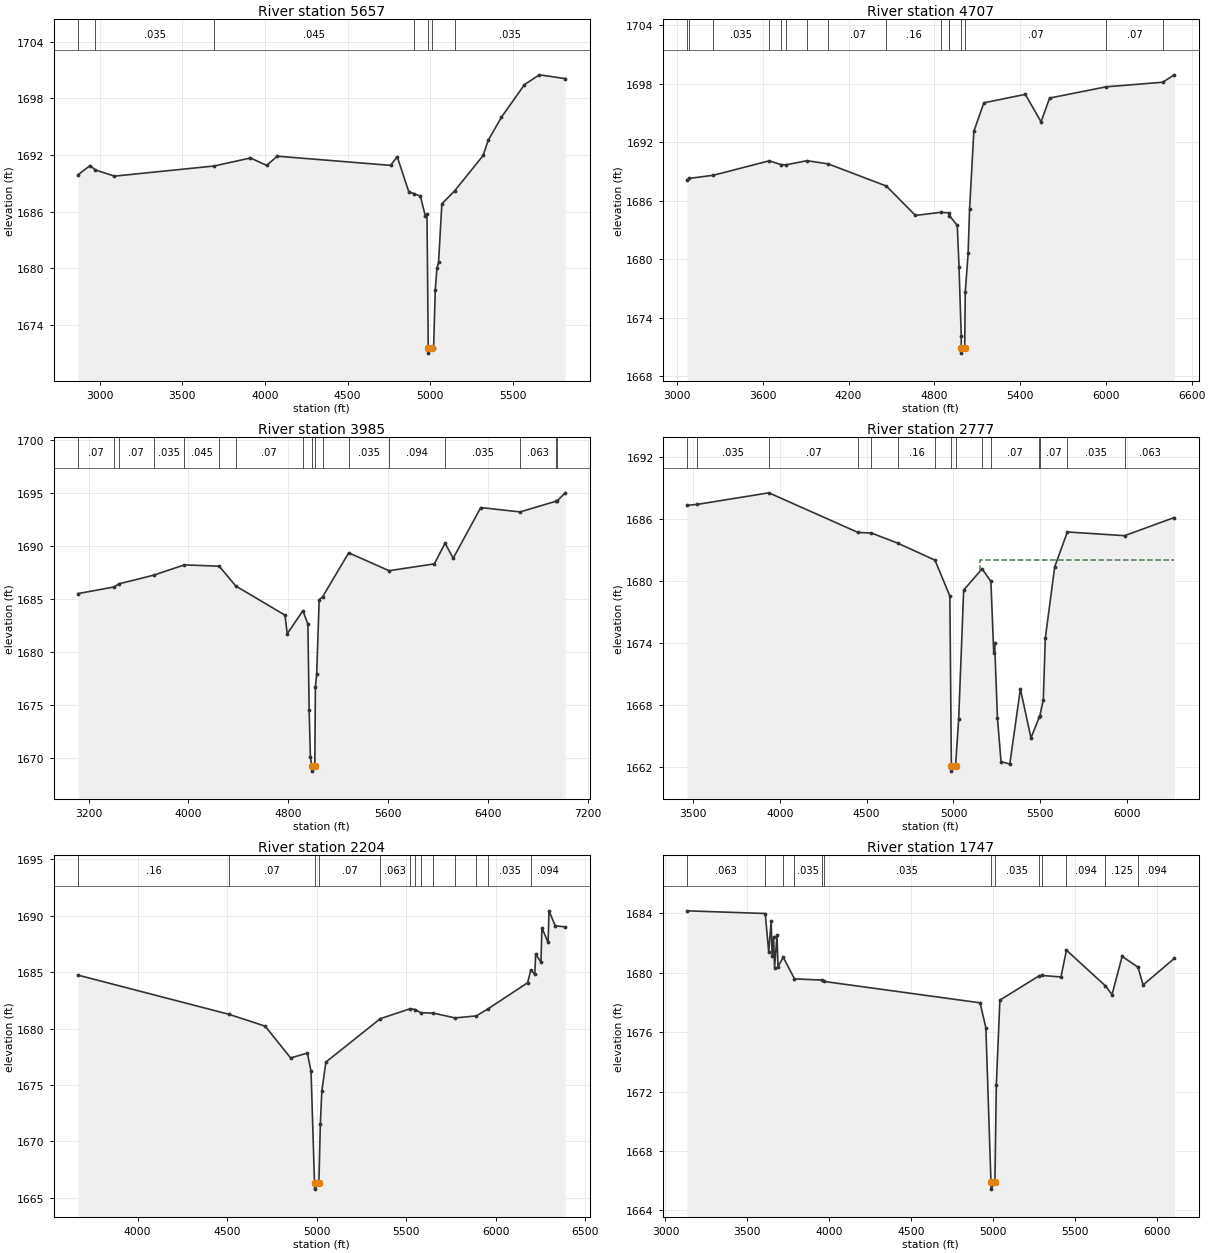
Type RM Length L Ch R = 1,5657,950,950,950
BEGIN DESCRIPTION:
Cat Claw Creek 4.0
END DESCRIPTION:
XS GIS Cut Line= 3
      1580798.61      6859507.68      1582570.80      6860187.22
      1583621.29      6860184.66
#Sta/Elev= 30
  2868.0 1689.90  2941.6 1690.89  2974.4 1690.42  3089.0 1689.77  3691.3 1690.84
  3912.3 1691.69  4010.1 1690.91  4074.4 1691.88  4759.8 1690.91  4800.2 1691.82
  4870.2 1688.11  4904.6 1687.91  4940.2 1687.65  4970.2 1685.55  4980.2 1685.73
  4988.0 1671.54  4988.5 1671.04  5012.0 1671.54  5020.2 1671.54  5030.2 1677.69
  5040.2 1680.00  5050.2 1680.65  5070.2 1686.84  5147.0 1688.20  5320.2 1691.96
  5350.2 1693.55  5430.2 1695.99  5570.2 1699.46  5660.2 1700.49  5816.5 1700.09
#Mann=7,-1,0
  2868.0   0.094       0  2974.4   0.035       0  3691.3   0.045       0
  4904.6    0.07       0  4988.0    0.07       0  5012.0    0.07       0
  5147.0   0.035       0
Bank Sta=4988,5012
Exp/Cntr=0.3,0.1

Type RM Length L Ch R = 1,4707,722,722,722
BEGIN DESCRIPTION:
Cat Claw Creek 3.0
END DESCRIPTION:
XS GIS Cut Line= 3
      1581000.74      6860085.23      1582648.92      6861090.20
      1584127.31      6861129.06
#Sta/Elev= 30
  3069.6 1688.15  3086.5 1688.28  3254.1 1688.60  3645.3 1690.08  3723.9 1689.70
  3759.3 1689.66  3908.5 1690.09  4057.7 1689.76  4464.0 1687.49  4667.5 1684.48
  4848.3 1684.81  4900.0 1684.73  4904.9 1684.47  4960.3 1683.46  4972.4 1679.22
  4987.9 1672.13  4988.0 1670.87  4988.5 1670.37  5012.0 1670.87  5016.1 1676.65
  5036.1 1680.58  5046.1 1685.09  5076.1 1693.10  5146.1 1696.02  5436.2 1696.89
  5546.3 1694.07  5606.3 1696.51  6001.2 1697.66  6397.1 1698.13  6478.9 1698.89
#Mann=16,-1,0
  3069.6   0.035       0  3086.5   0.094       0  3254.1   0.035       0
  3645.3    0.07       0  3723.9   0.045       0  3759.3    0.07       0
  3908.5   0.045       0  4057.7    0.07       0  4464.0    0.16       0
  4848.3    0.07       0  4900.0    0.16       0  4904.9    0.07       0
  4988.0    0.07       0  5012.0    0.07       0  6001.2    0.07       0
  6397.1   0.035       0
Bank Sta=4988,5012
Exp/Cntr=0.3,0.1

Type RM Length L Ch R = 1,3985,1208,1208,1208
BEGIN DESCRIPTION:
Cat Claw Creek 2.6
END DESCRIPTION:
XS GIS Cut Line= 3
      1580803.11      6861100.18      1582435.81      6861737.90
      1584579.27      6861911.43
#Sta/Elev= 30
  3114.5 1685.54  3404.6 1686.17  3442.4 1686.46  3721.3 1687.28  3967.2 1688.25
  4246.4 1688.13  4378.7 1686.26  4773.3 1683.51  4791.3 1681.75  4916.7 1683.93
  4956.8 1682.66  4966.8 1674.57  4976.9 1670.08  4988.0 1669.29  4988.5 1668.79
  5012.1 1669.29  5017.0 1676.70  5027.0 1677.92  5047.1 1684.96  5074.1 1685.23
  5283.7 1689.39  5607.0 1687.70  5970.1 1688.35  6055.6 1690.30  6120.6 1688.88
  6341.3 1693.66  6657.0 1693.25  6945.4 1694.26  6955.1 1694.31  7017.8 1695.05
#Mann=17,-1,0
  3114.5    0.07       0  3404.6   0.035       0  3442.4    0.07       0
  3721.3   0.035       0  3967.2   0.045       0  4246.4   0.035       0
  4378.7    0.07       0  4916.7   0.035       0  4988.0   0.035       0
  5012.1   0.035       0  5074.1    0.07       0  5283.7   0.035       0
  5607.0   0.094       0  6055.6   0.035       0  6657.0   0.063       0
  6945.4   0.035       0  6955.1   0.063       0
Bank Sta=4988,5012.1
Exp/Cntr=0.3,0.1

Type RM Length L Ch R = 1,2777,573,573,573
BEGIN DESCRIPTION:
Cat Claw Creek 2.4
END DESCRIPTION:
XS GIS Cut Line= 3
      1581650.09      6862134.66      1582708.61      6862661.44
      1584308.43      6862942.09
#Sta/Elev= 30
  3465.6 1687.31  3524.6 1687.40  3936.9 1688.52  4450.6 1684.68  4527.2 1684.63
  4680.0 1683.64  4893.6 1682.00  4979.3 1678.52  4987.9 1662.07  4988.4 1661.57
  5012.1 1662.07  5030.1 1666.66  5058.8 1679.10  5164.8 1681.16  5215.6 1679.94
  5231.9 1673.05  5237.0 1673.96  5253.4 1666.73  5273.8 1662.49  5324.5 1662.26
  5385.4 1669.53  5446.4 1664.78  5494.3 1666.81  5498.0 1666.95  5517.4 1668.47
  5528.9 1674.43  5583.2 1681.36  5656.0 1684.73  5985.3 1684.37  6272.2 1686.13
#Mann=15,-1,0
  3465.6   0.045       0  3524.6   0.035       0  3936.9    0.07       0
  4450.6    0.16       0  4527.2    0.07       0  4680.0    0.16       0
  4893.6    0.07       0  4987.9    0.07       0  5012.1    0.07       0
  5164.8    0.16       0  5215.6    0.07       0  5494.3   0.035       0
  5498.0    0.07       0  5656.0   0.035       0  5985.3   0.063       0
#XS Ineff=2,0
       0                 5152.00    0.00 1682.00
Permanent Ineff=
       F       F
Bank Sta=4987.9,5012.1
Exp/Cntr=0.3,0.1

Type RM Length L Ch R = 1,2204,457,457,457
BEGIN DESCRIPTION:
Cat Claw Creek 2.3
END DESCRIPTION:
XS GIS Cut Line= 3
      1581751.14      6862698.54      1582809.66      6863225.34
      1584294.78      6863627.22
#Sta/Elev= 30
  3666.7 1684.73  4509.8 1681.26  4712.3 1680.21  4854.6 1677.39  4947.8 1677.83
  4968.6 1676.20  4987.9 1666.28  4988.4 1665.78  5012.2 1666.28  5020.4 1671.54
  5028.5 1674.43  5051.4 1677.03  5355.1 1680.87  5521.6 1681.75  5550.4 1681.68
  5580.1 1681.40  5652.2 1681.36  5772.7 1680.94  5892.0 1681.12  5957.5 1681.75
  6177.7 1684.05  6195.9 1685.19  6217.6 1684.79  6222.8 1686.60  6252.3 1685.87
  6257.5 1688.92  6292.1 1687.62  6297.3 1690.42  6332.0 1689.09  6387.6 1689.00
#Mann=13,-1,0
  3666.7    0.16       0  4509.8    0.07       0  4987.9    0.07       0
  5012.2    0.07       0  5355.1   0.063       0  5521.6    0.07       0
  5550.4   0.094       0  5580.1   0.063       0  5652.2   0.094       0
  5772.7   0.125       0  5892.0   0.094       0  5957.5   0.035       0
  6195.9   0.094       0
Bank Sta=4987.9,5012.2
Exp/Cntr=0.3,0.1

Type RM Length L Ch R = 1,1747,1166,1166,1166
BEGIN DESCRIPTION:
Cat Claw Creek 2.0
END DESCRIPTION:
XS GIS Cut Line= 3
      1581229.84      6862798.95      1582115.26      6863413.42
      1583893.77      6864077.22
#Sta/Elev= 30
  3131.8 1684.16  3609.3 1683.98  3630.5 1681.38  3645.4 1683.48  3651.5 1681.13
  3660.2 1682.38  3666.3 1680.33  3681.2 1682.51  3687.3 1680.40  3719.1 1681.04
  3788.0 1679.58  3955.5 1679.50  3966.7 1679.41  4921.2 1677.97  4956.8 1676.29
  4987.9 1665.93  4988.4 1665.43  5012.2 1665.93  5020.5 1672.41  5042.4 1678.15
  5282.7 1679.79  5300.0 1679.81  5415.4 1679.71  5448.9 1681.51  5687.1 1679.11
  5727.2 1678.52  5789.0 1681.09  5885.8 1680.37  5917.1 1679.17  6107.9 1680.96
#Mann=13,-1,0
  3131.8   0.063       0  3609.3   0.094       0  3719.1   0.063       0
  3788.0   0.035       0  3955.5   0.063       0  3966.7   0.035       0
  4987.9   0.035       0  5012.2   0.035       0  5282.7   0.063       0
  5300.0   0.035       0  5448.9   0.094       0  5687.1   0.125       0
  5885.8   0.094       0
Bank Sta=4987.9,5012.2
Exp/Cntr=0.3,0.1

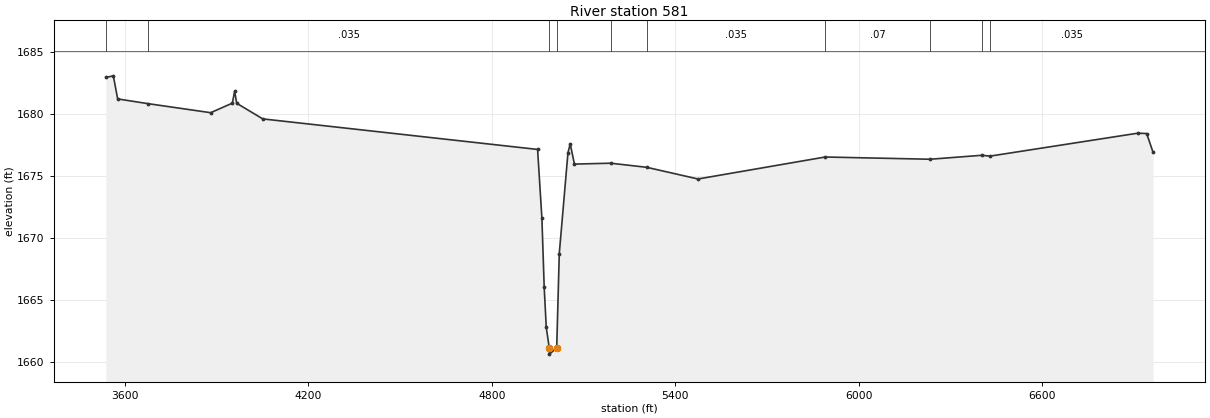
Type RM Length L Ch R = 1,581,0,0,0
BEGIN DESCRIPTION:
Cat Claw Creek 1.0
END DESCRIPTION:
XS GIS Cut Line= 3
      1581004.01      6862724.61      1582136.40      6863969.71
      1583648.22      6864833.28
#Sta/Elev= 30
  3538.1 1682.94  3562.4 1683.07  3576.6 1681.21  3675.4 1680.83  3880.7 1680.10
  3951.6 1680.87  3959.1 1681.83  3965.8 1680.86  4051.0 1679.60  4949.7 1677.14
  4963.8 1671.59  4971.3 1666.03  4978.0 1662.81  4987.9 1661.15  4988.4 1660.65
  5012.2 1661.15  5020.6 1668.75  5049.0 1676.87  5056.4 1677.59  5070.1 1675.96
  5188.8 1676.03  5306.5 1675.70  5474.2 1674.76  5890.1 1676.53  6233.0 1676.35
  6403.1 1676.67  6428.6 1676.60  6912.4 1678.45  6941.3 1678.42  6962.2 1676.91
#Mann=10,-1,0
  3538.1   0.063       0  3675.4   0.035       0  4987.9   0.035       0
  5012.2   0.035       0  5188.8    0.07       0  5306.5   0.035       0
  5890.1    0.07       0  6233.0   0.035       0  6403.1   0.063       0
  6428.6   0.035       0
Bank Sta=4987.9,5012.2
Exp/Cntr=0.3,0.1

Chan Stop Cuts=-1