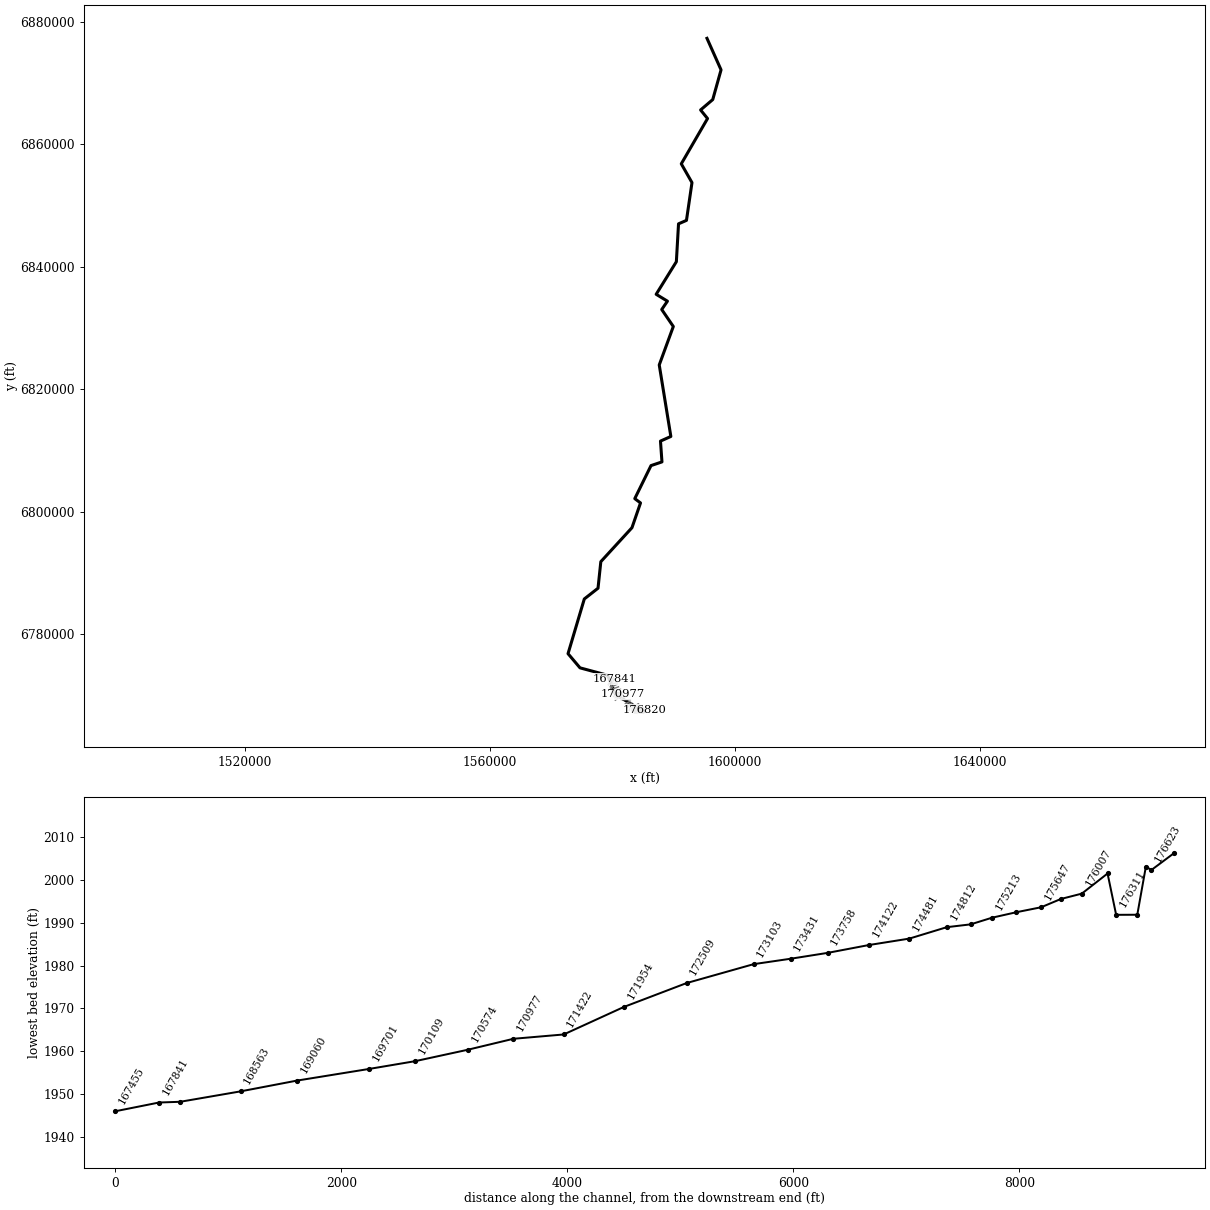
--- Cedar Creek.prj (project) ---

Proj Title=Cedar Creek Base Level Engineering
Current Plan=p01
Default Exp/Contr=0.3,0.1
English Units
Geom File=g01
Flow File=f01
Plan File=p01
BEGIN DESCRIPTION:
Cedar Creek
END DESCRIPTION:

--- Cedar Creek.p01 (plan) ---

Plan Title=Multiple Run
Short Identifier=Multiple
Geom File=g01
Flow File=f01
Subcritical Flow
K Sum by GR= 0
Std Step Tol= 0.01
Critical Tol= 0.01
Num of Std Step Trials= 20
Max Error Tol= 0.3
Flow Tol Ratio= 0.001
Split Flow NTrial= 30
Split Flow Tol= 0.02
Split Flow Ratio= 0.02
Log Output Level= 0
Friction Slope Method= 1
Unsteady Friction Slope Method= 2
Unsteady Bridges Friction Slope Method= 1
Parabolic Critical Depth
Global Vel Dist=  1 , 1 , 1
Global Log Level= 0
CheckData=True
Encroach Param= -1, 0, 0, 0
BEGIN DESCRIPTION:
Multiple Run
END DESCRIPTION:

--- Cedar Creek.f01 (steady flow) ---

Flow Title=Multiple
Number of Profiles=7
Profile Names=10-year,25-year,50-year,1pct_min,100-year,1pct_plu,500-year
River Rch & RM= Cedar Creek,Reach-1,176820
      80     103     122      89     143     197     200
River Rch & RM= Cedar Creek,Reach-1,174481
     282     395     491     378     605     833     934
River Rch & RM= Cedar Creek,Reach-1,167841
     374     533     667     518     830    1140    1300
River Rch & RM= Cedar Creek,Reach-1,165753
     456     654     822     640    1030    1410    1620
River Rch & RM= Cedar Creek,Reach-1,161046
     660     959    1220     954    1530    2100    2450
River Rch & RM= Cedar Creek,Reach-1,158156
    1050    1550    2000    1580    2540    3490    4160
River Rch & RM= Cedar Creek,Reach-1,155708
    1620    2460    3230    2610    4190    5770    7150
River Rch & RM= Cedar Creek,Reach-1,147917
    1860    2820    3690    2980    4770    6570    8090
River Rch & RM= Cedar Creek,Reach-1,136080
    1920    2900    3790    3050    4890    6730    8260
River Rch & RM= Cedar Creek,Reach-1,128767
    1930    2910    3790    3040    4870    6700    8170
River Rch & RM= Cedar Creek,Reach-1,123994
    1970    2960    3850    3080    4930    6780    8200
River Rch & RM= Cedar Creek,Reach-1,110549
    1930    2880    3720    2960    4740    6520    7810
River Rch & RM= Cedar Creek,Reach-1,93881
    2350    3520    4560    3630    5820    8000    9610
River Rch & RM= Cedar Creek,Reach-1,83077
    2350    3490    4500    3570    5720    7880    9380
River Rch & RM= Cedar Creek,Reach-1,60072
    2730    4080    5270    4190    6720    9240   11100
River Rch & RM= Cedar Creek,Reach-1,58286
    2820    4200    5420    4300    6900    9490   11300
River Rch & RM= Cedar Creek,Reach-1,47172
    4560    7070    9390    8050   12900   17800   21300
River Rch & RM= Cedar Creek,Reach-1,30534
    4530    7010    9310    7990   12800   17600   21100
River Rch & RM= Cedar Creek,Reach-1,24223
    4470    6920    9180    7880   12600   17400   20700
River Rch & RM= Cedar Creek,Reach-1,14028
    5360    8150   10700    8770   14100   19300   23200
River Rch & RM= Cedar Creek,Reach-1,7277
    5820    8750   11400    9100   14600   20100   24200
River Rch & RM= Cedar Creek,Reach-1,3473
    5870    8820   11500    9160   14700   20200   24300
Boundary for River Rch & Prof#=Cedar Creek,Reach-1,1
Up Type=0
Dn Type=3
Dn Slope=0.0001
Boundary for River Rch & Prof#=Cedar Creek,Reach-1,2
Up Type=0
Dn Type=3
Dn Slope=0.0001
Boundary for River Rch & Prof#=Cedar Creek,Reach-1,3
Up Type=0
Dn Type=3
Dn Slope=0.0001
Boundary for River Rch & Prof#=Cedar Creek,Reach-1,4
Up Type=0
Dn Type=3
Dn Slope=0.0001
Boundary for River Rch & Prof#=Cedar Creek,Reach-1,5
Up Type=0
Dn Type=3
Dn Slope=0.0001
Boundary for River Rch & Prof#=Cedar Creek,Reach-1,6
Up Type=0
Dn Type=3
Dn Slope=0.0001
Boundary for River Rch & Prof#=Cedar Creek,Reach-1,7
Up Type=0
Dn Type=3
Dn Slope=0.0001

--- Cedar Creek.g01 (geometry) ---

Geom Title=Existing Conditions

River Reach=Cedar Creek,Reach-1
Reach XY= 30
      1585105.00      6767338.00      1580509.96      6770143.11
      1579207.45      6773282.54      1574710.44      6774490.17
      1572754.01      6776807.05      1575414.01      6785745.02
      1577653.87      6787500.03      1578112.07      6791838.01
      1583199.54      6797385.55      1584597.21      6801434.57
      1583658.61      6802136.50      1586310.58      6807533.24
      1588100.03      6808135.41      1587858.54      6811536.54
      1589552.88      6812293.27      1587656.38      6823978.34
      1589955.61      6830258.61      1588062.80      6833034.58
      1588994.48      6834397.79      1587154.64      6835519.74
      1590452.64      6840843.52      1590807.34      6847032.51
      1592103.76      6847597.70      1593004.93      6853767.97
      1591258.42      6856836.78      1595547.23      6864234.59
      1594408.54      6865636.54      1596397.55      6867331.95
      1597755.00      6872188.00      1595455.00      6877338.00

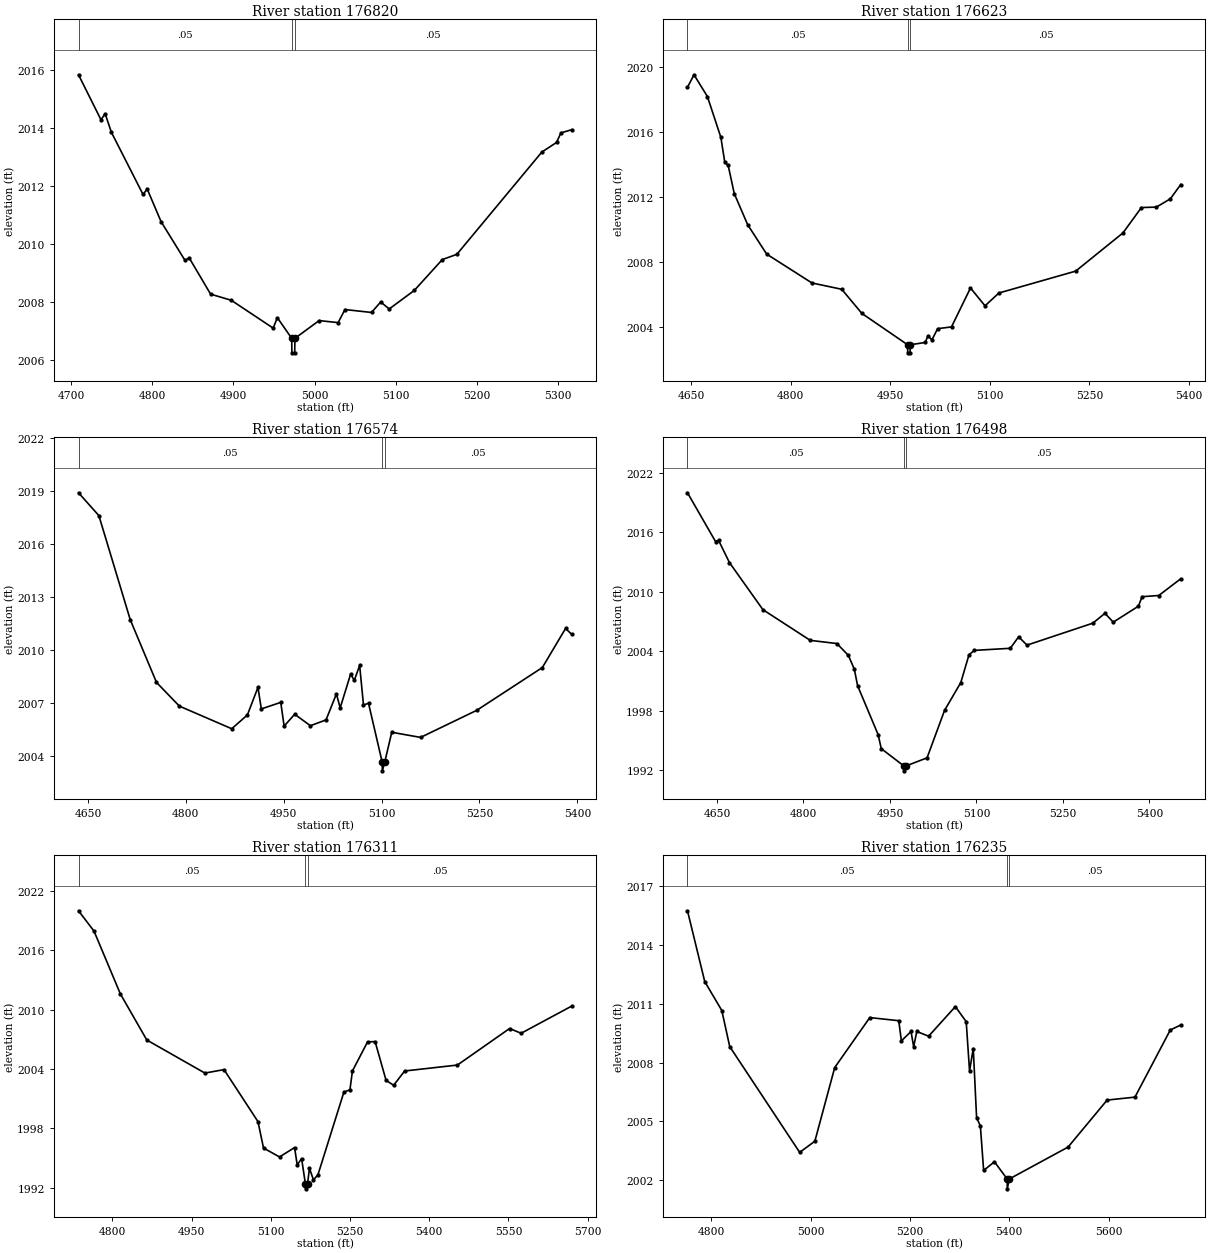
Type RM Length L Ch R = 1,176820,197,197,197
BEGIN DESCRIPTION:
Cedar Creek 176470.516
END DESCRIPTION:
XS GIS Cut Line= 3
      1585034.26      6767068.23      1585089.53      6767353.63
      1585215.76      6767644.30
#Sta/Elev= 30
  4709.3 2015.83  4737.0 2014.28  4742.1 2014.49  4749.8 2013.85  4788.8 2011.71
  4793.9 2011.90  4810.9 2010.78  4840.5 2009.44  4845.6 2009.53  4872.0 2008.28
  4897.4 2008.07  4949.1 2007.11  4954.2 2007.47  4971.9 2006.76  4972.1 2006.26
  4975.6 2006.26  4975.9 2006.76  5005.7 2007.37  5029.1 2007.30  5037.5 2007.75
  5070.2 2007.65  5081.5 2008.01  5092.0 2007.77  5123.0 2008.41  5157.4 2009.47
  5175.3 2009.65  5280.0 2013.17  5298.1 2013.50  5303.5 2013.83  5316.9 2013.94
#Mann=3,-1,0
  4709.3    0.05       0  4971.9    0.05       0  4975.9    0.05       0
Bank Sta=4971.9,4975.9
Exp/Cntr=0.3,0.1

Type RM Length L Ch R = 1,176623,49,49,49
BEGIN DESCRIPTION:
Cedar Creek 176623.2
END DESCRIPTION:
XS GIS Cut Line= 3
      1584871.28      6767088.31      1584925.98      6767442.51
      1585148.65      6767756.34
#Sta/Elev= 30
  4644.3 2018.76  4654.1 2019.53  4674.3 2018.19  4694.6 2015.67  4700.5 2014.13
  4705.6 2013.94  4714.8 2012.20  4735.0 2010.28  4763.6 2008.47  4831.8 2006.69
  4876.7 2006.30  4907.1 2004.81  4975.9 2002.88  4976.1 2002.38  4979.6 2002.38
  4979.9 2002.88  5002.7 2003.02  5006.5 2003.43  5012.6 2003.18  5021.2 2003.87
  5042.1 2003.98  5070.7 2006.38  5092.6 2005.28  5113.5 2006.07  5229.2 2007.42
  5300.5 2009.78  5328.2 2011.34  5350.9 2011.37  5371.8 2011.88  5387.5 2012.76
#Mann=3,-1,0
  4644.3    0.05       0  4975.9    0.05       0  4979.9    0.05       0
Bank Sta=4975.9,4979.9
Exp/Cntr=0.3,0.1

Type RM Length L Ch R = 1,176574,76,76,76
BEGIN DESCRIPTION:
Cedar Creek 176574.06
END DESCRIPTION:
XS GIS Cut Line= 4
      1584789.25      6767107.83      1584883.01      6767460.74
      1584918.16      6767523.24      1585104.34      6767782.33
#Sta/Elev= 30
  4635.6 2018.89  4666.8 2017.60  4714.9 2011.71  4755.1 2008.17  4790.1 2006.83
  4870.4 2005.55  4894.4 2006.33  4910.6 2007.89  4915.7 2006.67  4945.5 2007.04
  4950.7 2005.70  4966.9 2006.37  4990.9 2005.72  5014.9 2006.05  5030.8 2007.52
  5036.6 2006.73  5052.5 2008.63  5058.3 2008.29  5066.4 2009.13  5072.3 2006.89
  5080.0 2006.99  5100.9 2003.67  5101.2 2003.17  5104.9 2003.67  5115.6 2005.35
  5159.8 2005.06  5245.8 2006.59  5346.4 2009.01  5382.0 2011.22  5391.5 2010.88
#Mann=3,-1,0
  4635.6    0.05       0  5100.9    0.05       0  5104.9    0.05       0
Bank Sta=5100.9,5104.9
Exp/Cntr=0.3,0.1

Type RM Length L Ch R = 1,176498,187,187,187
BEGIN DESCRIPTION:
Cedar Creek 176497.71
END DESCRIPTION:
XS GIS Cut Line= 4
      1584717.65      6767097.50      1584816.60      6767489.39
      1584875.20      6767580.53      1585083.55      6767852.70
#Sta/Elev= 30
  4599.0 2019.98  4647.7 2015.05  4652.8 2015.19  4671.7 2012.94  4729.8 2008.18
  4811.9 2005.08  4858.1 2004.76  4878.0 2003.56  4888.3 2002.17  4894.0 2000.50
  4929.6 1995.56  4935.0 1994.15  4974.1 1992.41  4974.3 1991.91  4978.1 1992.41
  5014.4 1993.22  5044.8 1998.02  5072.9 2000.82  5087.1 2003.62  5096.3 2004.07
  5158.7 2004.28  5173.2 2005.44  5187.7 2004.60  5302.0 2006.82  5322.8 2007.81
  5337.3 2006.92  5380.9 2008.53  5387.2 2009.49  5416.2 2009.61  5454.3 2011.30
#Mann=3,-1,0
  4599.0    0.05       0  4974.1    0.05       0  4978.1    0.05       0
Bank Sta=4974.1,4978.1
Exp/Cntr=0.3,0.1

Type RM Length L Ch R = 1,176311,76,76,76
BEGIN DESCRIPTION:
Cedar Creek 176311.13
END DESCRIPTION:
XS GIS Cut Line= 5
      1584672.07      6767098.74      1584678.58      6767365.69
      1584700.72      6767514.13      1584785.35      6767561.00
      1585058.78      6767880.00
#Sta/Elev= 30
  4735.9 2019.97  4765.2 2017.92  4815.2 2011.57  4865.2 2006.92  4975.2 2003.58
  5011.4 2003.93  5075.7 1998.68  5086.2 1996.01  5116.5 1995.11  5145.0 1996.06
  5150.0 1994.30  5158.3 1994.95  5165.5 1992.39  5165.7 1991.89  5169.5 1992.39
  5173.2 1993.96  5180.8 1992.79  5189.2 1993.30  5238.4 2001.66  5249.8 2001.89
  5254.6 2003.80  5283.2 2006.73  5297.5 2006.76  5318.3 2002.84  5332.6 2002.35
  5353.4 2003.79  5453.3 2004.39  5552.1 2008.08  5574.0 2007.60  5669.9 2010.35
#Mann=3,-1,0
  4735.9    0.05       0  5165.5    0.05       0  5169.5    0.05       0
Bank Sta=5165.5,5169.5
Exp/Cntr=0.3,0.1

Type RM Length L Ch R = 1,176235,228,228,228
BEGIN DESCRIPTION:
Cedar Creek 176234.52
END DESCRIPTION:
XS GIS Cut Line= 5
      1584582.23      6767093.57      1584610.87      6767343.55
      1584629.10      6767486.78      1584675.98      6767609.18
      1585026.23      6767916.46
#Sta/Elev= 30
  4752.2 2015.75  4786.9 2012.14  4821.3 2010.66  4837.2 2008.82  4978.1 2003.42
  5008.6 2003.99  5048.6 2007.75  5119.2 2010.30  5177.5 2010.14  5182.8 2009.11
  5202.2 2009.59  5207.5 2008.81  5213.8 2009.59  5237.6 2009.35  5291.5 2010.86
  5313.3 2010.09  5320.0 2007.58  5327.5 2008.72  5334.2 2005.19  5341.8 2004.77
  5348.4 2002.50  5370.2 2002.94  5395.8 2002.06  5396.0 2001.56  5399.8 2002.06
  5518.3 2003.69  5597.0 2006.09  5653.0 2006.24  5724.2 2009.67  5745.2 2009.92
#Mann=3,-1,0
  4752.2    0.05       0  5395.8    0.05       0  5399.8    0.05       0
Bank Sta=5395.8,5399.8
Exp/Cntr=0.3,0.1

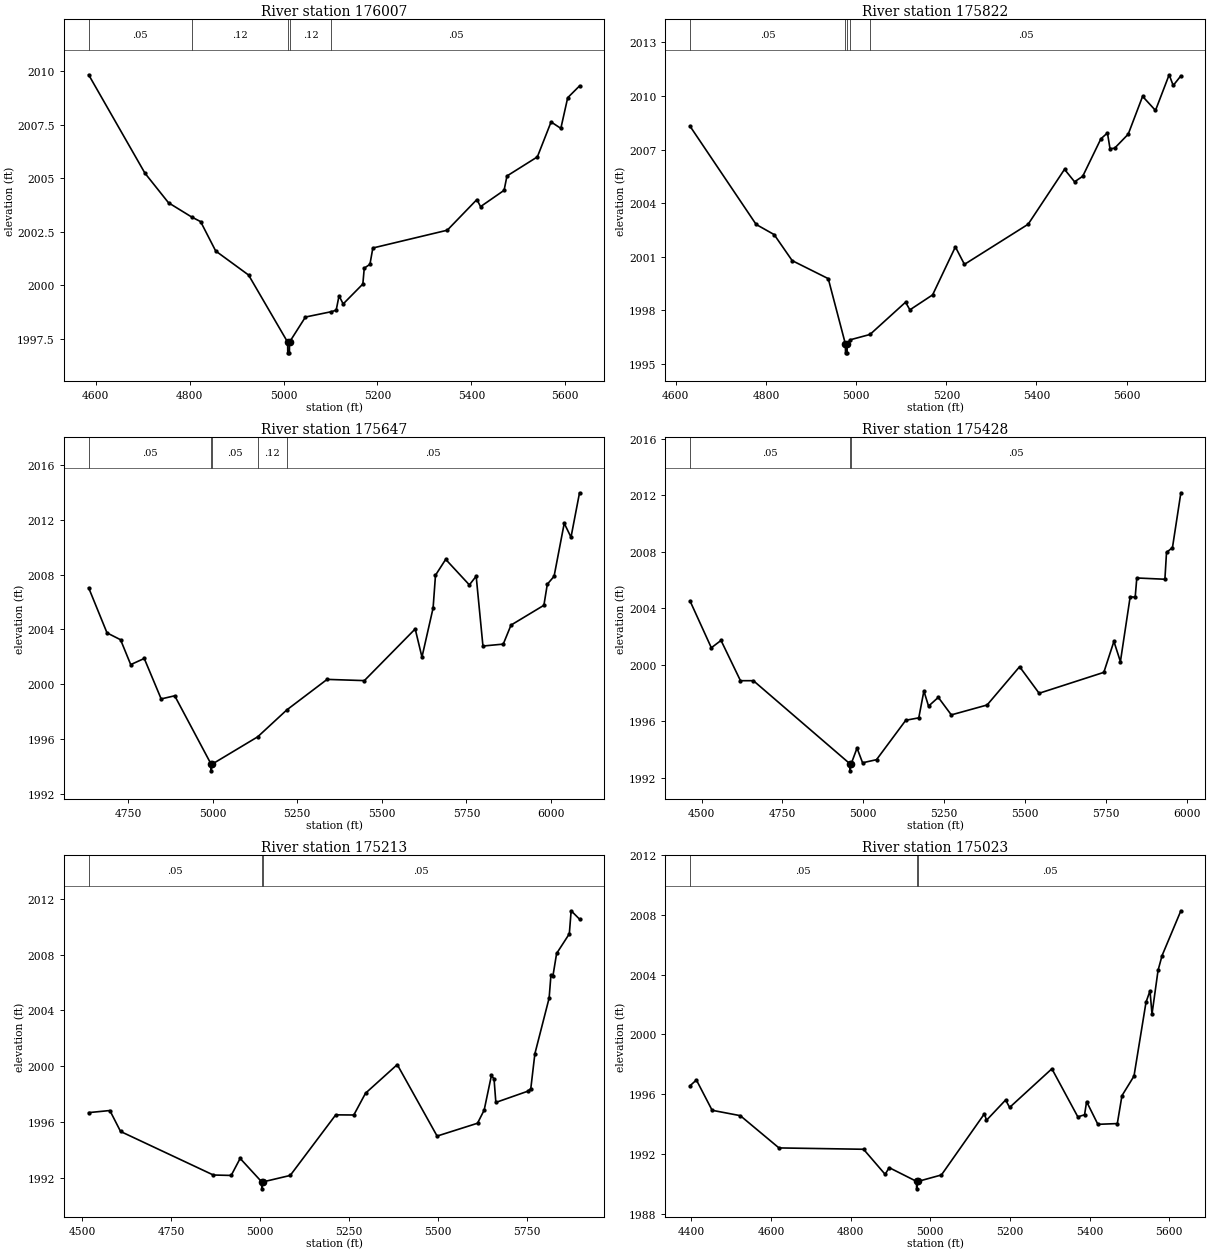
Type RM Length L Ch R = 1,176007,185,185,185
BEGIN DESCRIPTION:
Cedar Creek 176007.01
END DESCRIPTION:
XS GIS Cut Line= 4
      1584506.71      6767128.70      1584547.07      6767545.38
      1584643.43      6767684.70      1585010.34      6767957.93
#Sta/Elev= 30
  4584.9 2009.82  4704.8 2005.23  4755.0 2003.85  4804.0 2003.19  4823.4 2002.97
  4855.5 2001.60  4925.5 2000.48  5008.7 1997.35  5009.0 1996.85  5012.5 1996.85
  5012.7 1997.35  5046.6 1998.52  5102.0 1998.77  5112.1 1998.84  5118.2 1999.51
  5127.0 1999.13  5168.9 2000.06  5171.9 2000.80  5184.0 2000.98  5190.2 2001.74
  5348.7 2002.57  5411.8 2004.00  5419.6 2003.67  5469.7 2004.43  5475.9 2005.10
  5540.6 2005.99  5569.8 2007.62  5590.6 2007.32  5605.2 2008.75  5630.4 2009.30
#Mann=5,-1,0
  4584.9    0.05       0  4804.0    0.12       0  5008.7    0.07       0
  5012.7    0.12       0  5102.0    0.05       0
Bank Sta=5008.7,5012.7
Exp/Cntr=0.3,0.1

Type RM Length L Ch R = 1,175822,175,175,175
BEGIN DESCRIPTION:
Cedar Creek 175821.96
END DESCRIPTION:
XS GIS Cut Line= 3
      1584392.88      6767171.29      1584396.03      6767539.88
      1584491.73      6768253.80
#Sta/Elev= 30
  4631.4 2008.31  4778.1 2002.80  4818.1 2002.23  4858.1 2000.77  4938.1 1999.76
  4976.1 1996.10  4976.4 1995.60  4979.9 1995.60  4980.1 1996.10  4986.7 1996.33
  5030.7 1996.63  5109.6 1998.44  5119.2 1998.01  5169.6 1998.85  5220.1 2001.54
  5240.2 2000.56  5381.5 2002.81  5462.2 2005.89  5484.5 2005.19  5502.6 2005.50
  5542.9 2007.60  5557.4 2007.93  5563.1 2007.05  5573.2 2007.07  5603.5 2007.86
  5635.4 2009.98  5664.0 2009.19  5694.3 2011.19  5703.3 2010.59  5720.3 2011.13
#Mann=5,-1,0
  4631.4    0.05       0  4976.1    0.07       0  4980.1    0.05       0
  4986.7    0.12       0  5030.7    0.05       0
Bank Sta=4976.1,4980.1
Exp/Cntr=0.3,0.1

Type RM Length L Ch R = 1,175647,219,219,219
BEGIN DESCRIPTION:
Cedar Creek 175647.25
END DESCRIPTION:
XS GIS Cut Line= 3
      1584221.15      6767173.68      1584221.86      6767541.60
      1584268.89      6768623.16
#Sta/Elev= 30
  4633.7 2007.05  4688.0 2003.75  4728.0 2003.25  4758.0 2001.43  4798.0 2001.88
  4848.0 1998.92  4888.0 1999.15  4995.3 1994.16  4995.6 1993.66  4999.3 1994.16
  5133.3 1996.15  5219.4 1998.12  5338.3 2000.35  5448.4 2000.26  5598.6 2004.04
  5618.6 2001.98  5651.5 2005.57  5658.6 2007.97  5688.7 2009.13  5758.7 2007.26
  5778.8 2007.90  5798.8 2002.79  5858.8 2002.93  5881.7 2004.32  5978.9 2005.77
  5989.0 2007.31  6009.0 2007.89  6039.0 2011.77  6059.0 2010.75  6084.2 2014.00
#Mann=5,-1,0
  4633.7    0.05       0  4995.3    0.05       0  4999.3    0.05       0
  5133.3    0.12       0  5219.4    0.05       0
Bank Sta=4995.3,4999.3
Exp/Cntr=0.3,0.1

Type RM Length L Ch R = 1,175428,215,215,215
BEGIN DESCRIPTION:
Cedar Creek 175364.42
END DESCRIPTION:
XS GIS Cut Line= 3
      1584010.65      6767052.14      1584039.84      6767587.35
      1584145.11      6768563.89
#Sta/Elev= 30
  4464.0 2004.53  4530.0 2001.21  4560.0 2001.73  4620.1 1998.88  4660.1 1998.88
  4958.6 1993.00  4958.8 1992.50  4962.6 1993.00  4980.6 1994.11  4997.8 1993.07
  5040.9 1993.29  5131.4 1996.08  5171.6 1996.25  5187.4 1998.15  5201.8 1997.08
  5232.0 1997.70  5272.2 1996.46  5382.9 1997.16  5483.4 1999.87  5543.8 1997.99
  5743.9 1999.47  5775.1 2001.66  5795.2 2000.23  5825.4 2004.82  5840.9 2004.79
  5845.9 2006.15  5932.8 2006.06  5937.8 2007.96  5956.2 2008.30  5982.2 2012.18
#Mann=3,-1,0
  4464.0    0.05       0  4958.6    0.05       0  4962.6    0.05       0
Bank Sta=4958.6,4962.6
Exp/Cntr=0.3,0.1

Type RM Length L Ch R = 1,175213,190,190,190
BEGIN DESCRIPTION:
Cedar Creek 175211.98
END DESCRIPTION:
XS GIS Cut Line= 3
      1583782.78      6767108.56      1583825.68      6767598.08
      1583995.45      6768471.34
#Sta/Elev= 30
  4517.9 1996.68  4577.6 1996.83  4607.7 1995.33  4868.7 1992.21  4918.9 1992.18
  4944.1 1993.40  5004.7 1991.72  5005.0 1991.22  5008.7 1991.72  5085.0 1992.18
  5213.0 1996.52  5263.9 1996.51  5296.8 1998.07  5386.1 2000.12  5498.2 1995.00
  5611.9 1995.92  5630.6 1996.86  5651.0 1999.34  5658.4 1999.09  5663.5 1997.41
  5752.9 1998.21  5761.8 1998.40  5773.3 2000.90  5813.4 2004.89  5818.5 2006.54
  5824.2 2006.49  5834.4 2008.08  5870.2 2009.49  5875.3 2011.14  5898.9 2010.54
#Mann=3,-1,0
  4517.9    0.05       0  5004.7    0.05       0  5008.7    0.05       0
Bank Sta=5004.7,5008.7
Exp/Cntr=0.3,0.1

Type RM Length L Ch R = 1,175023,211,211,211
BEGIN DESCRIPTION:
Cedar Creek 175022.93
END DESCRIPTION:
XS GIS Cut Line= 3
      1583598.33      6767112.92      1583683.66      6767711.74
      1583758.67      6768334.87
#Sta/Elev= 30
  4396.7 1996.56  4412.8 1996.95  4452.3 1994.92  4523.0 1994.56  4620.1 1992.40
  4832.5 1992.31  4886.7 1990.63  4896.8 1991.08  4965.5 1990.16  4965.7 1989.66
  4969.5 1990.16  5028.0 1990.59  5136.0 1994.69  5141.1 1994.25  5189.2 1995.61
  5199.2 1995.11  5305.3 1997.70  5370.5 1994.48  5387.4 1994.62  5392.5 1995.50
  5420.8 1993.98  5469.6 1994.03  5481.3 1995.90  5511.5 1997.21  5541.7 2002.16
  5551.7 2002.92  5556.7 2001.36  5571.9 2004.29  5582.0 2005.28  5629.2 2008.28
#Mann=3,-1,0
  4396.7    0.05       0  4965.5    0.05       0  4969.5    0.05       0
Bank Sta=4965.5,4969.5
Exp/Cntr=0.3,0.1

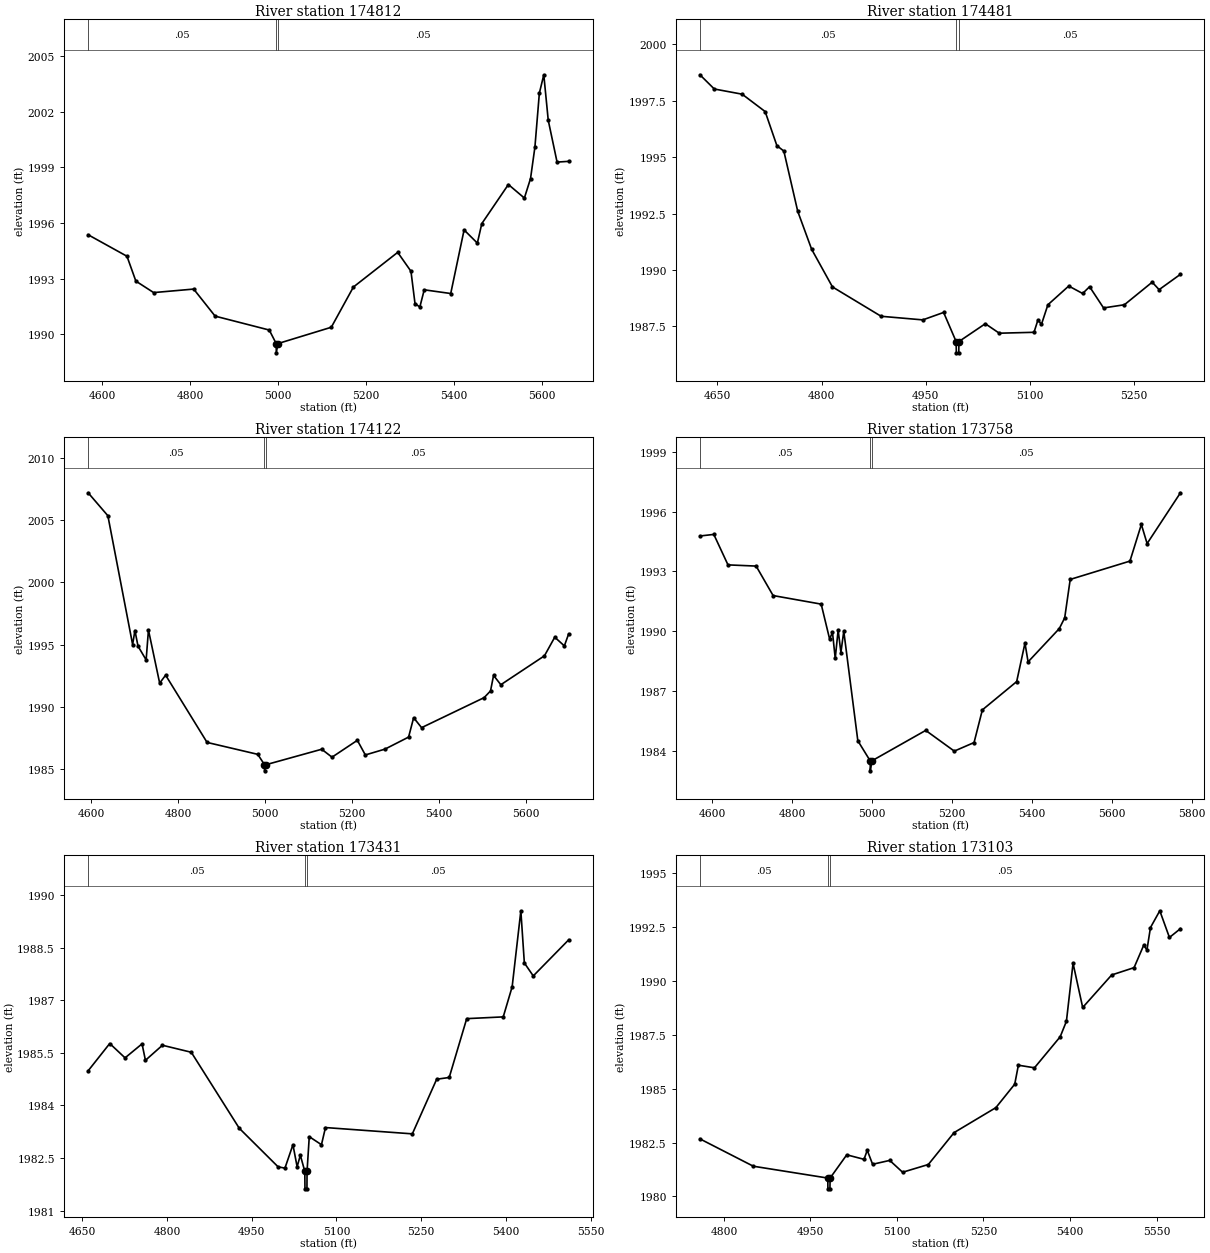
Type RM Length L Ch R = 1,174812,331,331,331
BEGIN DESCRIPTION:
Cedar Creek 174811.89
END DESCRIPTION:
XS GIS Cut Line= 3
      1583415.16      6767310.66      1583481.53      6767738.04
      1583562.16      6768394.20
#Sta/Elev= 30
  4567.5 1995.37  4655.9 1994.21  4676.1 1992.87  4716.6 1992.25  4807.7 1992.44
  4856.5 1990.98  4979.7 1990.23  4995.5 1989.50  4995.7 1989.00  4999.5 1989.50
  5120.9 1990.38  5171.2 1992.55  5272.0 1994.42  5302.2 1993.40  5311.4 1991.66
  5322.4 1991.47  5332.4 1992.40  5392.7 1992.20  5423.1 1995.63  5453.3 1994.92
  5463.4 1995.97  5523.9 1998.08  5560.3 1997.35  5574.3 1998.40  5584.3 2000.10
  5594.4 2003.01  5604.5 2004.00  5614.6 2001.55  5634.7 1999.29  5661.1 1999.33
#Mann=3,-1,0
  4567.5    0.05       0  4995.5   0.035       0  4999.5    0.05       0
Bank Sta=4995.5,4999.5
Exp/Cntr=0.3,0.1

Type RM Length L Ch R = 1,174481,359,359,359
BEGIN DESCRIPTION:
Cedar Creek 174481
END DESCRIPTION:
XS GIS Cut Line= 3
      1583198.09      6767517.26      1583205.91      6767894.90
      1583217.62      6768208.66
#Sta/Elev= 30
  4624.8 1998.65  4645.5 1998.02  4685.6 1997.79  4718.7 1997.02  4735.6 1995.51
  4745.6 1995.27  4765.6 1992.60  4785.6 1990.92  4815.6 1989.25  4885.6 1987.95
  4945.6 1987.79  4975.6 1988.12  4993.6 1986.83  4993.9 1986.33  4997.4 1986.33
  4997.6 1986.83  5035.6 1987.62  5055.7 1987.20  5105.7 1987.24  5111.4 1987.79
  5116.4 1987.59  5125.7 1988.46  5155.7 1989.29  5175.7 1988.96  5185.7 1989.26
  5205.8 1988.32  5235.8 1988.46  5275.8 1989.46  5285.8 1989.13  5316.5 1989.81
#Mann=3,-1,0
  4624.8    0.05       0  4993.6    0.05       0  4997.6    0.05       0
Bank Sta=4993.6,4997.6
Exp/Cntr=0.3,0.1

Type RM Length L Ch R = 1,174122,364,364,364
BEGIN DESCRIPTION:
Cedar Creek 174121.83
END DESCRIPTION:
XS GIS Cut Line= 3
      1582755.21      6767569.67      1582889.75      6767955.93
      1583160.51      6768597.09
#Sta/Elev= 30
  4592.6 2007.23  4638.0 2005.38  4694.9 1995.00  4700.2 1996.13  4707.3 1994.87
  4726.0 1993.76  4731.3 1996.17  4757.1 1991.89  4770.8 1992.53  4866.1 1987.11
  4982.6 1986.15  4998.1 1985.32  4998.3 1984.82  5002.1 1985.32  5129.7 1986.56
  5153.4 1985.92  5211.7 1987.28  5230.0 1986.10  5275.2 1986.57  5329.5 1987.54
  5341.1 1989.10  5359.4 1988.30  5503.2 1990.72  5517.9 1991.26  5524.9 1992.51
  5541.6 1991.76  5641.9 1994.09  5665.6 1995.59  5687.7 1994.89  5697.6 1995.86
#Mann=3,-1,0
  4592.6    0.05       0  4998.1    0.05       0  5002.1    0.05       0
Bank Sta=4998.1,5002.1
Exp/Cntr=0.3,0.1

Type RM Length L Ch R = 1,173758,327,327,327
BEGIN DESCRIPTION:
Cedar Creek 173758.48
END DESCRIPTION:
XS GIS Cut Line= 3
      1582334.22      6767899.52      1582646.70      6768198.99
      1583140.72      6768790.52
#Sta/Elev= 30
  4568.5 1994.78  4603.3 1994.86  4638.8 1993.33  4709.3 1993.27  4751.8 1991.79
  4872.2 1991.36  4893.3 1989.61  4900.5 1989.94  4907.4 1988.64  4914.7 1990.06
  4921.6 1988.93  4928.8 1990.00  4964.0 1984.50  4995.0 1983.49  4995.2 1982.99
  4999.0 1983.49  5134.0 1985.02  5205.6 1983.98  5255.1 1984.41  5275.9 1986.05
  5361.8 1987.47  5382.6 1989.40  5390.4 1988.46  5468.5 1990.13  5482.1 1990.67
  5495.9 1992.60  5645.5 1993.52  5674.1 1995.36  5688.5 1994.40  5772.0 1996.95
#Mann=3,-1,0
  4568.5    0.05       0  4995.0   0.035       0  4999.0    0.05       0
Bank Sta=4995,4999
Exp/Cntr=0.3,0.1

Type RM Length L Ch R = 1,173431,328,328,328
BEGIN DESCRIPTION:
Cedar Creek 173431.06
END DESCRIPTION:
XS GIS Cut Line= 3
      1582161.92      6768259.23      1582444.44      6768446.71
      1582888.46      6768701.92
#Sta/Elev= 30
  4660.1 1984.99  4698.4 1985.77  4725.5 1985.36  4755.6 1985.76  4761.6 1985.29
  4791.7 1985.72  4842.8 1985.52  4927.8 1983.35  4996.5 1982.25  5008.7 1982.21
  5022.9 1982.88  5030.3 1982.25  5036.0 1982.58  5043.9 1982.12  5044.2 1981.62
  5047.7 1981.62  5047.9 1982.12  5051.8 1983.11  5073.4 1982.88  5080.5 1983.37
  5234.4 1983.19  5277.5 1984.75  5299.7 1984.80  5330.7 1986.48  5395.4 1986.53
  5411.2 1987.39  5426.6 1989.56  5432.8 1988.07  5448.6 1987.70  5511.3 1988.73
#Mann=3,-1,0
  4660.1    0.05       0  5043.9   0.035       0  5047.9    0.05       0
Bank Sta=5043.9,5047.9
Exp/Cntr=0.3,0.1

Type RM Length L Ch R = 1,173103,594,594,594
BEGIN DESCRIPTION:
Cedar Creek 173102.51
END DESCRIPTION:
XS GIS Cut Line= 3
      1582101.16      6768617.40      1582311.63      6768731.86
      1582841.44      6768999.37
#Sta/Elev= 30
  4758.4 1982.67  4851.0 1981.40  4980.1 1980.85  4980.3 1980.35  4983.8 1980.35
  4984.1 1980.85  5013.0 1981.93  5042.9 1981.72  5048.5 1982.14  5057.8 1981.49
  5087.5 1981.67  5109.8 1981.12  5154.4 1981.48  5199.0 1982.96  5271.5 1984.12
  5304.2 1985.21  5310.5 1986.09  5338.4 1985.97  5383.0 1987.41  5393.8 1988.13
  5405.3 1990.82  5422.0 1988.77  5472.3 1990.28  5511.1 1990.62  5527.8 1991.66
  5533.4 1991.44  5539.5 1992.48  5555.7 1993.26  5572.4 1992.02  5591.5 1992.43
#Mann=3,-1,0
  4758.4    0.05       0  4980.1   0.035       0  4984.1    0.05       0
Bank Sta=4980.1,4984.1
Exp/Cntr=0.3,0.1

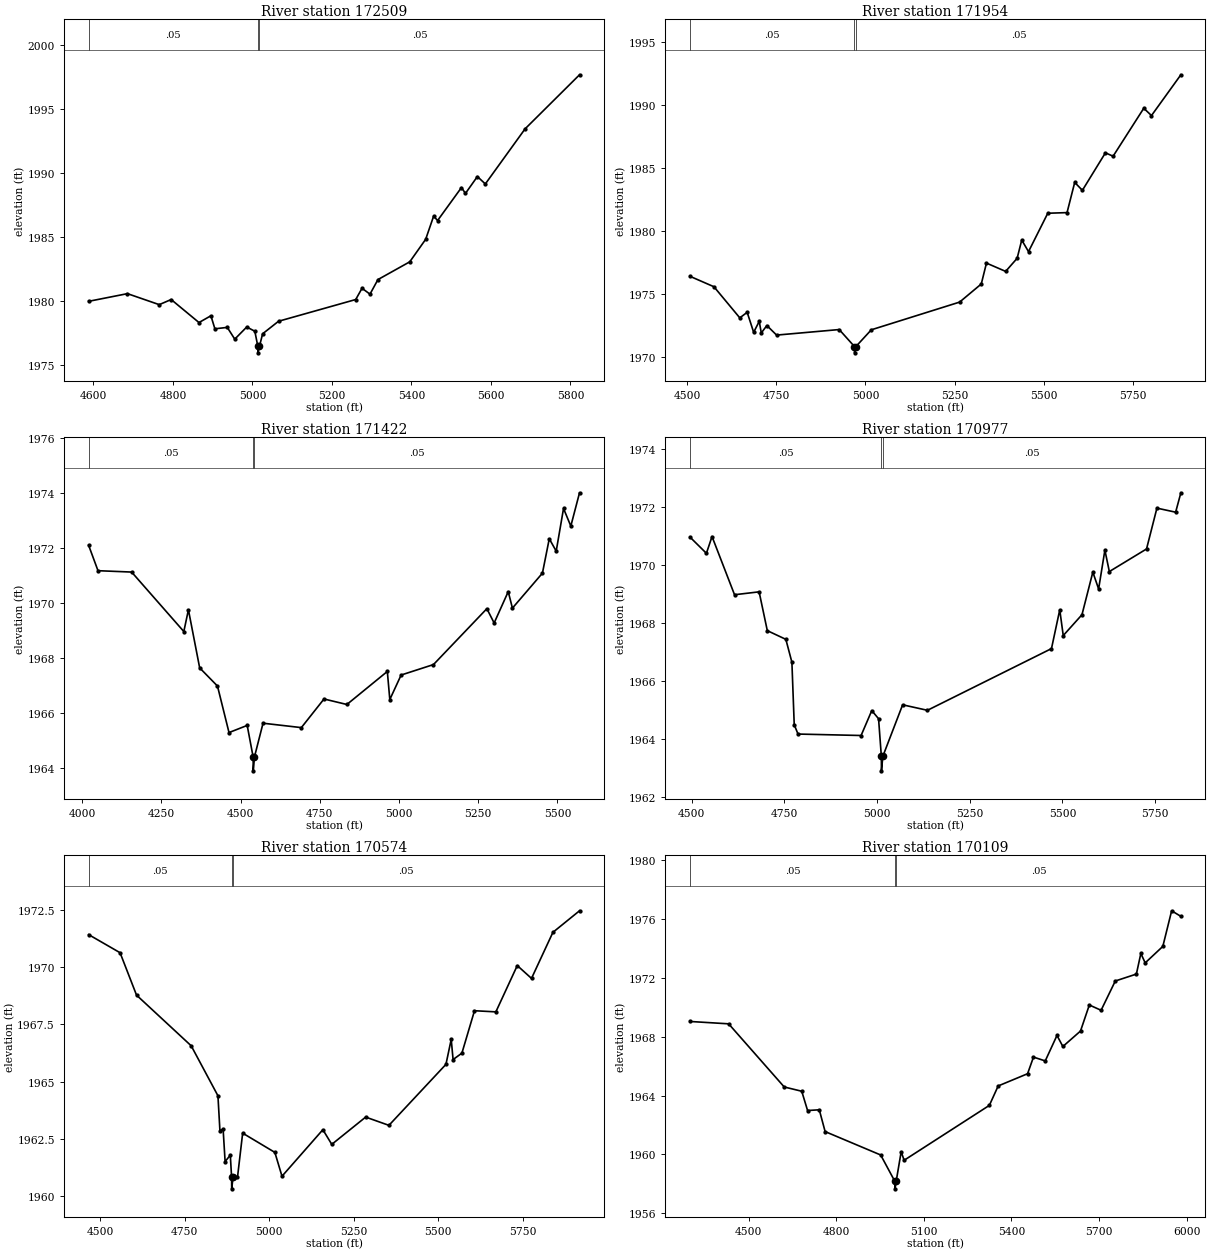
Type RM Length L Ch R = 1,172509,555,555,555
BEGIN DESCRIPTION:
Cedar Creek 172509.19
END DESCRIPTION:
XS GIS Cut Line= 3
      1581717.42      6769256.38      1582130.80      6769264.31
      1582951.87      6769292.03
#Sta/Elev= 30
  4588.0 1979.95  4685.6 1980.55  4765.6 1979.69  4795.6 1980.09  4865.6 1978.29
  4895.6 1978.82  4905.6 1977.80  4936.8 1977.91  4955.6 1976.99  4985.7 1977.94
  5006.1 1977.61  5013.7 1976.42  5013.9 1975.92  5017.7 1976.42  5025.7 1977.41
  5065.7 1978.39  5259.9 1980.09  5275.8 1980.97  5295.8 1980.51  5315.8 1981.65
  5395.9 1983.04  5435.9 1984.80  5455.9 1986.61  5465.9 1986.27  5526.0 1988.85
  5536.0 1988.39  5566.0 1989.71  5586.0 1989.13  5686.0 1993.44  5823.0 1997.67
#Mann=3,-1,0
  4588.0    0.05       0  5013.7   0.035       0  5017.7    0.05       0
Bank Sta=5013.7,5017.7
Exp/Cntr=0.3,0.1

Type RM Length L Ch R = 1,171954,532,532,532
BEGIN DESCRIPTION:
Cedar Creek 171954.37
END DESCRIPTION:
XS GIS Cut Line= 4
      1581431.00      6769313.02      1581475.23      6769480.22
      1581750.36      6769642.90      1582571.64      6769968.64
#Sta/Elev= 30
  4508.0 1976.41  4575.2 1975.58  4647.6 1973.11  4668.3 1973.55  4686.5 1971.96
  4702.1 1972.83  4707.9 1971.91  4723.5 1972.50  4750.8 1971.74  4926.3 1972.18
  4969.1 1970.83  4969.4 1970.33  4973.1 1970.83  5016.3 1972.16  5263.8 1974.36
  5324.6 1975.80  5339.1 1977.46  5392.9 1976.80  5425.1 1977.84  5438.0 1979.29
  5457.0 1978.37  5511.0 1981.42  5565.0 1981.47  5586.5 1983.87  5608.0 1983.24
  5672.6 1986.22  5694.1 1985.95  5780.1 1989.76  5801.7 1989.18  5884.1 1992.42
#Mann=3,-1,0
  4508.0    0.05       0  4969.1   0.035       0  4973.1    0.05       0
Bank Sta=4969.1,4973.1
Exp/Cntr=0.3,0.1

Type RM Length L Ch R = 1,171422,445,445,445
BEGIN DESCRIPTION:
Cedar Creek 171422.63
END DESCRIPTION:
XS GIS Cut Line= 3
      1580480.44      6769202.32      1581265.35      6769790.18
      1581758.84      6770072.74
#Sta/Elev= 30
  4020.3 1972.09  4049.8 1971.17  4156.0 1971.12  4320.7 1968.96  4335.2 1969.75
  4370.7 1967.64  4426.9 1966.98  4463.3 1965.29  4520.7 1965.55  4539.5 1964.40
  4539.8 1963.90  4543.5 1964.40  4570.7 1965.63  4691.6 1965.47  4763.1 1966.51
  4835.3 1966.31  4963.0 1967.51  4970.8 1966.49  5006.5 1967.38  5108.6 1967.76
  5277.1 1969.79  5300.1 1969.27  5344.6 1970.41  5357.8 1969.81  5452.5 1971.08
  5474.1 1972.33  5496.0 1971.88  5519.1 1973.43  5542.1 1972.79  5569.6 1974.00
#Mann=3,-1,0
  4020.3    0.05       0  4539.5   0.035       0  4543.5    0.05       0
Bank Sta=4539.5,4543.5
Exp/Cntr=0.3,0.1

Type RM Length L Ch R = 1,170977,403,403,403
BEGIN DESCRIPTION:
Cedar Creek 170977.49
END DESCRIPTION:
XS GIS Cut Line= 3
      1580435.66      6769576.45      1580883.62      6769809.54
      1581617.98      6770171.51
#Sta/Elev= 30
  4495.5 1970.96  4539.8 1970.40  4554.9 1970.98  4615.6 1968.97  4681.9 1969.07
  4704.0 1967.73  4754.0 1967.43  4770.3 1966.64  4776.6 1964.48  4786.8 1964.16
  4956.9 1964.11  4985.7 1964.97  5004.0 1964.69  5011.5 1963.39  5011.8 1962.89
  5015.5 1963.39  5068.9 1965.17  5135.8 1964.98  5470.3 1967.11  5492.6 1968.45
  5502.0 1967.56  5552.5 1968.28  5581.8 1969.75  5597.4 1969.17  5614.3 1970.51
  5626.3 1969.77  5726.6 1970.55  5754.6 1971.96  5805.1 1971.82  5819.2 1972.49
#Mann=3,-1,0
  4495.5    0.05       0  5011.5   0.035       0  5015.5    0.05       0
Bank Sta=5011.5,5015.5
Exp/Cntr=0.3,0.1

Type RM Length L Ch R = 1,170574,465,465,465
BEGIN DESCRIPTION:
Cedar Creek 170573.61
END DESCRIPTION:
XS GIS Cut Line= 3
      1580186.15      6769820.40      1580639.26      6770102.94
      1581509.69      6770393.09
#Sta/Elev= 30
  4466.1 1971.42  4559.0 1970.63  4607.7 1968.78  4769.3 1966.57  4848.4 1964.39
  4854.3 1962.86  4863.7 1962.94  4869.6 1961.52  4885.0 1961.80  4888.8 1960.83
  4889.1 1960.33  4893.0 1960.83  4906.2 1960.83  4921.5 1962.76  5016.7 1961.92
  5037.8 1960.88  5158.7 1962.91  5185.0 1962.27  5285.2 1963.46  5354.0 1963.10
  5522.6 1965.76  5538.2 1966.85  5543.7 1965.97  5569.8 1966.25  5607.0 1968.10
  5670.2 1968.05  5733.5 1970.07  5775.6 1969.51  5838.9 1971.52  5917.6 1972.46
#Mann=3,-1,0
  4466.1    0.05       0  4888.8   0.035       0  4893.0    0.05       0
Bank Sta=4888.8,4893
Exp/Cntr=0.3,0.1

Type RM Length L Ch R = 1,170109,408,408,408
BEGIN DESCRIPTION:
Cedar Creek 170109.09
END DESCRIPTION:
XS GIS Cut Line= 3
      1579952.73      6770356.42      1580650.63      6770392.87
      1581626.37      6770509.20
#Sta/Elev= 30
  4299.1 1969.03  4431.5 1968.87  4621.9 1964.58  4681.9 1964.29  4701.9 1962.98
  4742.0 1963.03  4762.0 1961.55  4952.3 1959.96  5001.1 1958.16  5001.4 1957.66
  5005.3 1958.16  5022.5 1960.18  5032.6 1959.60  5324.6 1963.33  5354.8 1964.65
  5455.5 1965.48  5475.7 1966.61  5516.0 1966.35  5556.2 1968.08  5576.4 1967.33
  5636.8 1968.38  5667.0 1970.15  5707.3 1969.79  5756.0 1971.78  5828.2 1972.25
  5843.5 1973.65  5858.4 1973.01  5918.8 1974.13  5949.0 1976.55  5980.6 1976.17
#Mann=3,-1,0
  4299.1    0.05       0  5001.1   0.035       0  5005.3    0.05       0
Bank Sta=5001.1,5005.3
Exp/Cntr=0.3,0.1

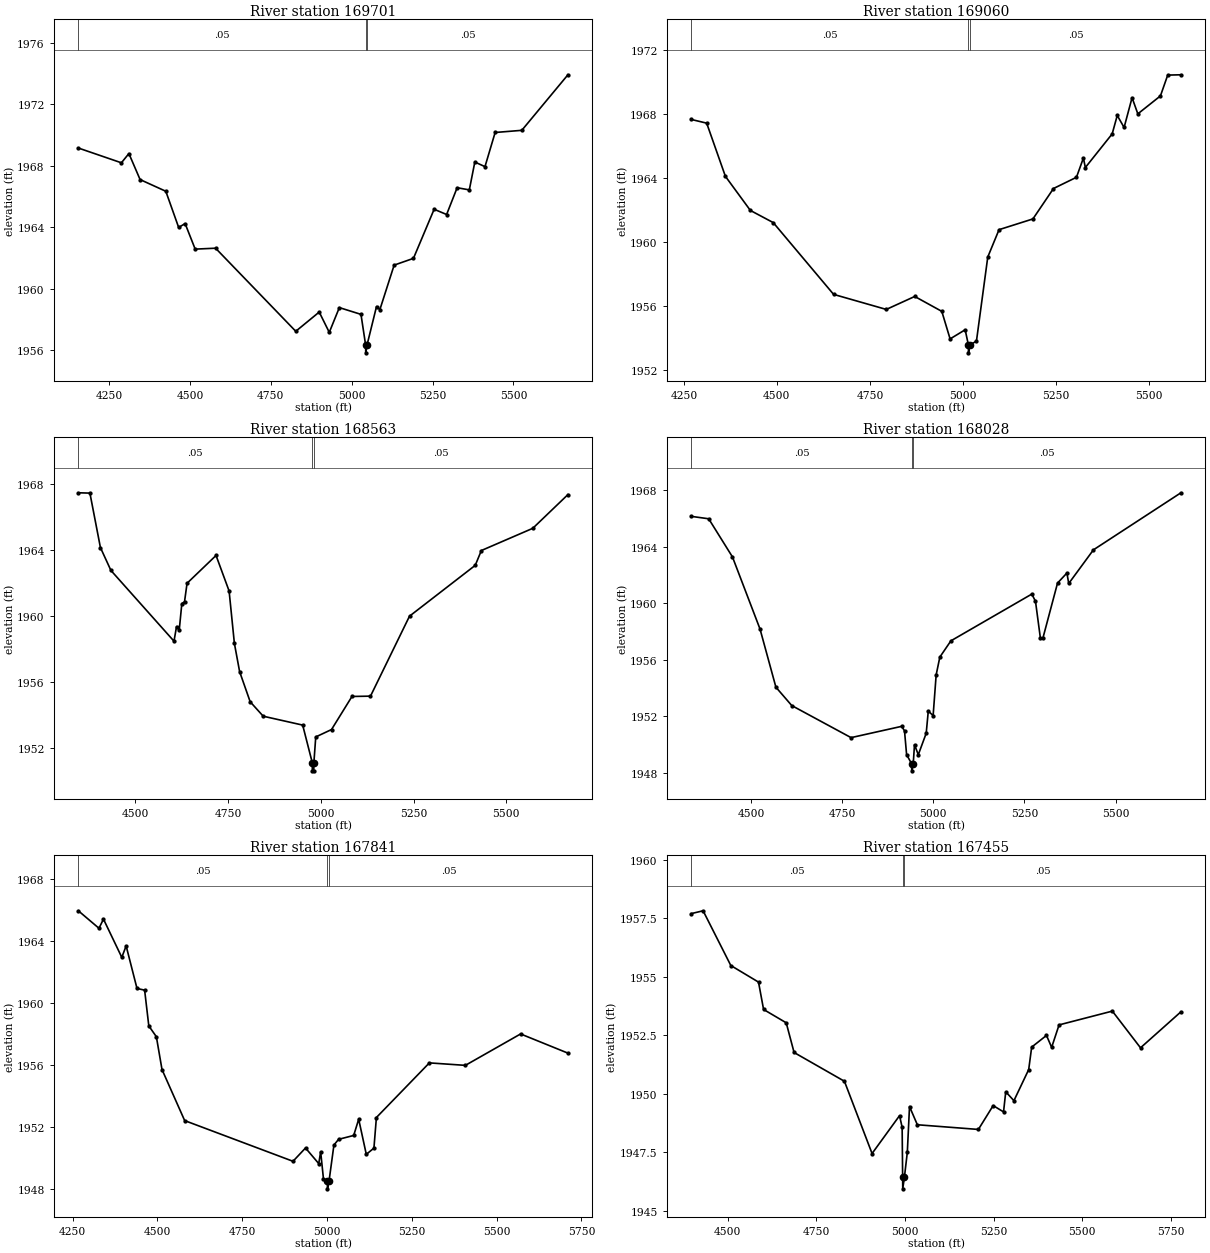
Type RM Length L Ch R = 1,169701,641,641,641
BEGIN DESCRIPTION:
Cedar Creek 169701.02
END DESCRIPTION:
XS GIS Cut Line= 3
      1579886.54      6770562.66      1580702.54      6770784.89
      1581339.67      6770984.53
#Sta/Elev= 30
  4155.0 1969.15  4288.1 1968.19  4311.3 1968.79  4345.9 1967.10  4425.4 1966.34
  4465.1 1963.99  4485.1 1964.24  4516.2 1962.58  4579.2 1962.64  4827.1 1957.24
  4899.6 1958.49  4930.7 1957.17  4961.8 1958.78  5028.7 1958.34  5043.1 1956.34
  5043.4 1955.84  5047.3 1956.34  5076.7 1958.85  5087.1 1958.65  5131.2 1961.54
  5190.9 1961.98  5254.8 1965.17  5293.4 1964.83  5325.9 1966.57  5363.6 1966.43
  5380.6 1968.24  5412.0 1967.94  5443.4 1970.16  5525.8 1970.30  5668.4 1973.91
#Mann=3,-1,0
  4155.0    0.05       0  5043.1   0.035       0  5047.3    0.05       0
Bank Sta=5043.1,5047.3
Exp/Cntr=0.3,0.1

Type RM Length L Ch R = 1,169060,497,497,497
BEGIN DESCRIPTION:
Cedar Creek 169059.99
END DESCRIPTION:
XS GIS Cut Line= 3
      1579796.49      6770862.93      1580447.55      6771188.46
      1580998.06      6771393.60
#Sta/Elev= 30
  4270.2 1967.67  4311.4 1967.44  4361.7 1964.12  4428.8 1961.99  4490.3 1961.23
  4652.4 1956.75  4794.0 1955.81  4870.4 1956.62  4943.1 1955.69  4965.4 1953.97
  5005.9 1954.54  5014.5 1953.60  5014.8 1953.10  5018.9 1953.60  5036.2 1953.83
  5066.6 1959.08  5096.9 1960.79  5187.9 1961.46  5243.2 1963.36  5304.9 1964.06
  5323.5 1965.26  5328.8 1964.67  5400.9 1966.77  5414.5 1967.92  5432.9 1967.17
  5454.3 1969.03  5469.8 1968.02  5530.5 1969.14  5550.1 1970.44  5585.6 1970.46
#Mann=3,-1,0
  4270.2    0.05       0  5014.5   0.035       0  5018.9    0.05       0
Bank Sta=5014.5,5018.9
Exp/Cntr=0.3,0.1

Type RM Length L Ch R = 1,168563,535,535,535
BEGIN DESCRIPTION:
Cedar Creek 168563.41
END DESCRIPTION:
XS GIS Cut Line= 3
      1579705.34      6771063.44      1580179.32      6771511.38
      1580771.55      6771817.88
#Sta/Elev= 30
  4346.9 1967.49  4378.1 1967.47  4406.4 1964.16  4434.7 1962.77  4604.6 1958.47
  4611.5 1959.36  4618.8 1959.16  4625.7 1960.75  4633.0 1960.87  4639.8 1961.99
  4717.9 1963.68  4753.1 1961.52  4767.3 1958.34  4781.4 1956.62  4809.8 1954.79
  4845.0 1953.91  4951.3 1953.37  4977.1 1951.09  4977.4 1950.59  4981.2 1950.59
  4981.5 1951.09  4986.5 1952.65  5029.0 1953.10  5084.1 1955.11  5134.0 1955.13
  5239.1 1959.99  5416.2 1963.08  5432.7 1963.98  5571.2 1965.33  5665.9 1967.38
#Mann=3,-1,0
  4346.9    0.05       0  4977.1   0.035       0  4981.5    0.05       0
Bank Sta=4977.1,4981.5
Exp/Cntr=0.3,0.1

Type RM Length L Ch R = 1,168028,187,187,187
BEGIN DESCRIPTION:
Cedar Creek 168329.457
END DESCRIPTION:
XS GIS Cut Line= 3
      1579786.11      6771362.97      1580107.35      6771943.97
      1580780.45      6772034.76
#Sta/Elev= 30
  4336.1 1966.16  4383.7 1965.99  4448.9 1963.29  4524.6 1958.18  4568.1 1954.07
  4611.6 1952.77  4774.3 1950.50  4913.2 1951.30  4920.9 1950.98  4926.6 1949.30
  4940.4 1948.65  4940.7 1948.15  4944.8 1948.65  4948.3 1950.00  4958.7 1949.29
  4980.4 1950.81  4986.1 1952.38  4999.4 1952.06  5007.7 1954.94  5017.8 1956.20
  5048.1 1957.35  5270.1 1960.66  5280.2 1960.15  5293.6 1957.55  5300.3 1957.52
  5340.7 1961.44  5366.4 1962.15  5371.4 1961.41  5439.1 1963.79  5679.2 1967.83
#Mann=3,-1,0
  4336.1    0.05       0  4940.4   0.035       0  4944.8    0.05       0
Bank Sta=4940.4,4944.8
Exp/Cntr=0.3,0.1

Type RM Length L Ch R = 1,167841,386,386,386
BEGIN DESCRIPTION:
Cedar Creek 167840.838
END DESCRIPTION:
XS GIS Cut Line= 3
      1579648.07      6771383.77      1579979.65      6772037.37
      1580293.55      6772674.32
#Sta/Elev= 30
  4267.1 1965.95  4327.9 1964.82  4341.2 1965.41  4395.2 1962.94  4408.0 1963.68
  4440.0 1960.93  4462.5 1960.82  4474.8 1958.51  4497.1 1957.81  4513.7 1955.69
  4580.5 1952.39  4899.8 1949.76  4936.7 1950.62  4975.7 1949.61  4981.3 1950.38
  4989.5 1948.64  5001.0 1948.48  5001.4 1947.98  5006.0 1948.48  5020.4 1950.81
  5034.1 1951.18  5078.7 1951.43  5093.4 1952.48  5115.8 1950.21  5138.3 1950.61
  5145.6 1952.59  5301.7 1956.12  5407.8 1955.96  5570.6 1957.99  5710.1 1956.75
#Mann=3,-1,0
  4267.1    0.05       0  5001.0   0.035       0  5006.0    0.05       0
Bank Sta=5001,5006
Exp/Cntr=0.3,0.1

Type RM Length L Ch R = 1,167455,1312,1312,1312
BEGIN DESCRIPTION:
Cedar Creek 167454.52
END DESCRIPTION:
XS GIS Cut Line= 3
      1579311.95      6771783.74      1579693.90      6772249.01
      1580155.72      6772877.51
#Sta/Elev= 30
  4396.9 1957.71  4430.1 1957.83  4508.3 1955.49  4586.5 1954.78  4600.8 1953.61
  4664.7 1953.04  4686.9 1951.77  4829.0 1950.54  4907.0 1947.45  4984.6 1949.07
  4991.9 1948.57  4993.3 1946.44  4993.6 1945.94  4998.3 1946.44  5006.5 1947.50
  5012.7 1949.46  5034.8 1948.68  5207.1 1948.48  5248.8 1949.50  5278.1 1949.23
  5284.3 1950.09  5307.4 1949.71  5349.1 1951.04  5357.5 1952.00  5399.3 1952.50
  5413.9 1951.99  5434.8 1952.95  5585.2 1953.54  5664.7 1951.97  5778.8 1953.51
#Mann=3,-1,0
  4396.9    0.05       0  4993.3   0.035       0  4998.3    0.05       0
Bank Sta=4993.3,4998.3
Exp/Cntr=0.3,0.1