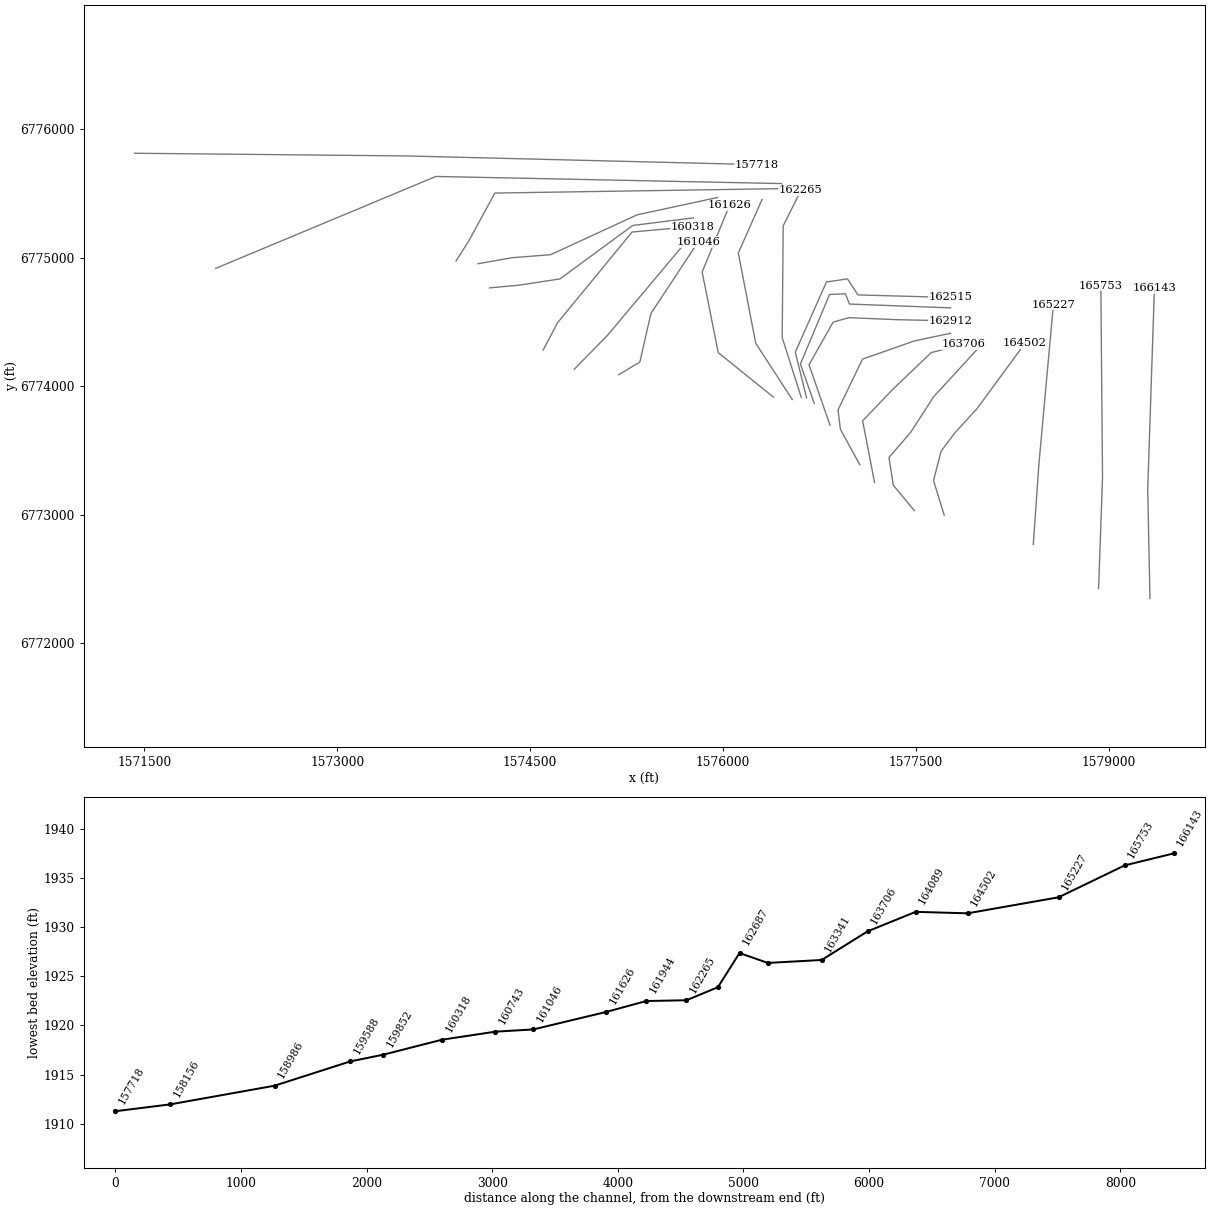
HEC-RAS study Cedar Creek.prj: Cedar Creek Base Level Engineering

--- Cedar Creek.g01 (geometry) --- (continued)

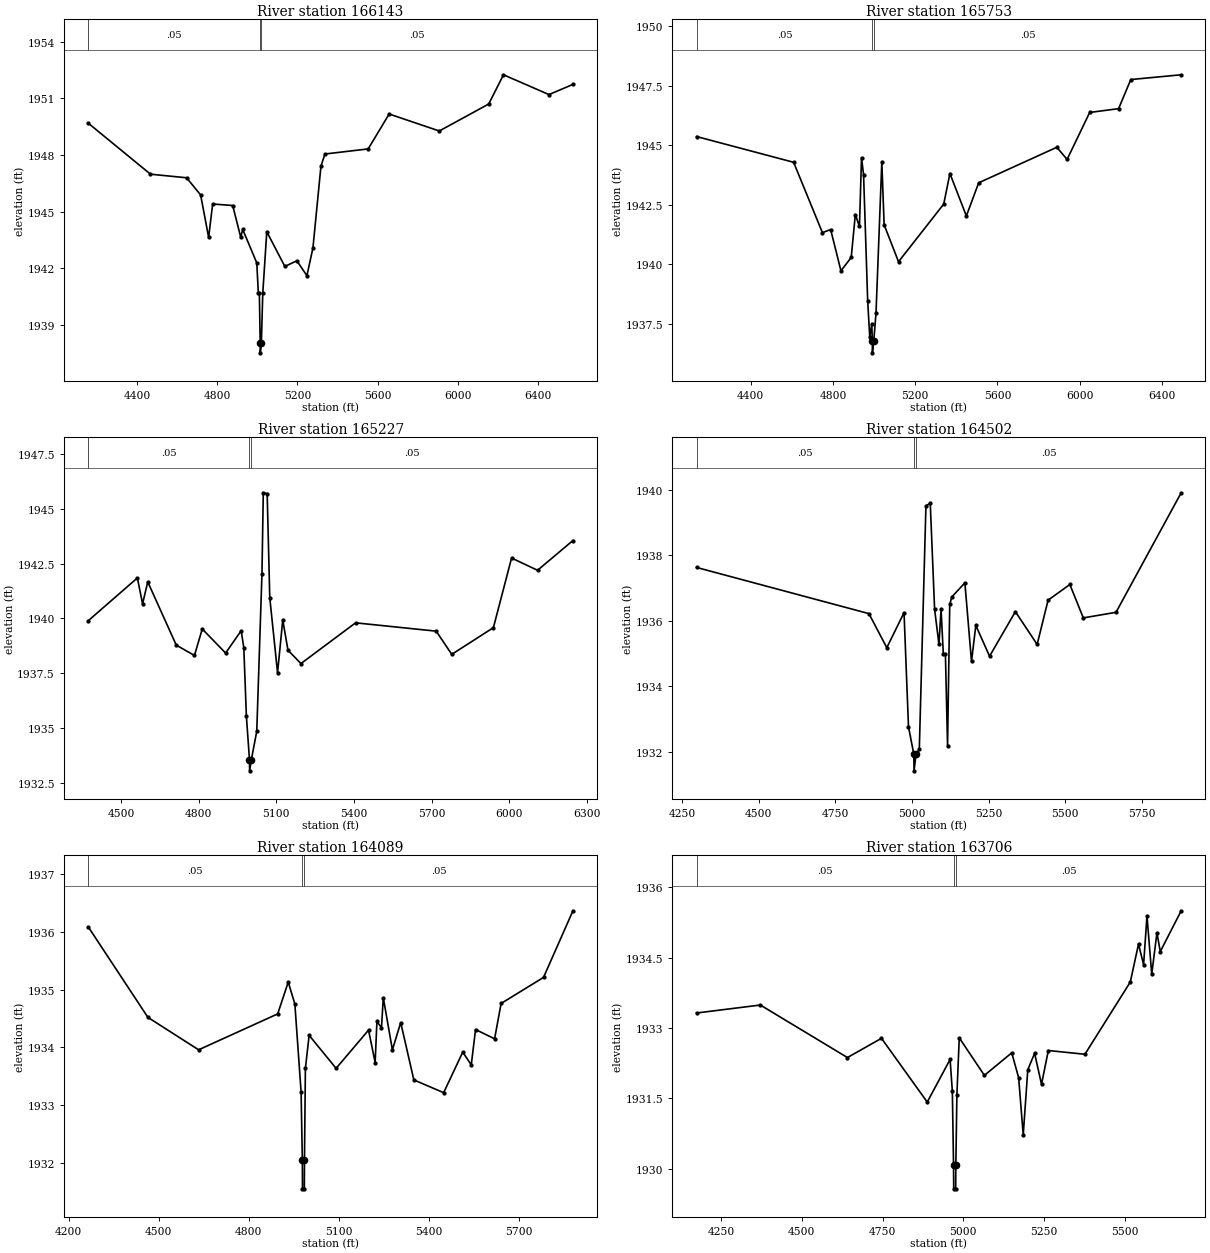
Type RM Length L Ch R = 1,166143,390,390,390
BEGIN DESCRIPTION:
Cedar Creek 166143.3
END DESCRIPTION:
XS GIS Cut Line= 3
      1579319.24      6772348.05      1579301.88      6773198.72
      1579353.92      6774764.31
#Sta/Elev= 30
  4157.2 1949.68  4467.2 1946.98  4647.3 1946.79  4717.3 1945.88  4757.3 1943.63
  4777.3 1945.40  4877.3 1945.32  4917.3 1943.64  4927.3 1944.05  4997.3 1942.28
  5005.2 1940.69  5010.2 1940.69  5014.5 1938.01  5014.9 1937.51  5020.2 1938.01
  5027.3 1940.67  5047.3 1943.93  5137.4 1942.09  5197.4 1942.39  5247.4 1941.60
  5277.5 1943.07  5317.5 1947.41  5337.5 1948.05  5553.0 1948.32  5657.7 1950.17
  5907.8 1949.27  6154.2 1950.70  6228.0 1952.25  6454.8 1951.20  6574.5 1951.74
#Mann=3,-1,0
  4157.2    0.05       0  5014.5    0.05       0  5020.2    0.05       0
Bank Sta=5014.5,5020.2
Exp/Cntr=0.3,0.1

Type RM Length L Ch R = 1,165753,526,526,526
BEGIN DESCRIPTION:
Cedar Creek 165753.24
END DESCRIPTION:
XS GIS Cut Line= 3
      1578919.94      6772426.13      1578950.32      6773294.21
      1578937.30      6774782.94
#Sta/Elev= 30
  4136.6 1945.36  4608.8 1944.28  4748.8 1941.33  4788.9 1941.46  4838.9 1939.73
  4888.9 1940.29  4908.9 1942.09  4929.0 1941.59  4939.0 1944.47  4949.0 1943.76
  4969.0 1938.47  4979.0 1936.96  4989.0 1937.49  4991.5 1936.79  4992.0 1936.29
  4998.6 1936.79  5009.6 1937.98  5037.8 1944.30  5049.0 1941.66  5119.0 1940.11
  5339.0 1942.53  5369.0 1943.81  5449.0 1942.03  5509.0 1943.42  5889.0 1944.91
  5939.0 1944.40  6049.0 1946.37  6189.6 1946.53  6249.0 1947.75  6494.0 1947.95
#Mann=3,-1,0
  4136.6    0.05       0  4991.5   0.035       0  4998.6    0.05       0
Bank Sta=4991.5,4998.6
Exp/Cntr=0.3,0.1

Type RM Length L Ch R = 1,165227,725,725,725
BEGIN DESCRIPTION:
Cedar Creek 165226.6
END DESCRIPTION:
XS GIS Cut Line= 3
      1578412.13      6772769.09      1578455.53      6773394.04
      1578568.27      6774634.17
#Sta/Elev= 30
  4374.3 1939.90  4563.7 1941.85  4583.7 1940.67  4603.8 1941.67  4714.0 1938.78
  4784.2 1938.31  4814.3 1939.52  4904.5 1938.42  4964.6 1939.44  4974.7 1938.67
  4984.7 1935.54  4996.7 1933.54  4997.2 1933.04  5003.8 1933.54  5024.8 1934.85
  5044.9 1942.05  5050.0 1945.74  5065.0 1945.70  5075.0 1940.95  5105.1 1937.52
  5125.2 1939.93  5145.3 1938.55  5195.5 1937.94  5406.4 1939.80  5717.8 1939.42
  5777.9 1938.36  5938.7 1939.58  6008.9 1942.76  6109.3 1942.20  6246.0 1943.56
#Mann=3,-1,0
  4374.3    0.05       0  4996.7    0.05       0  5003.8    0.05       0
Bank Sta=4996.7,5003.8
Exp/Cntr=0.3,0.1

Type RM Length L Ch R = 1,164502,413,413,413
BEGIN DESCRIPTION:
Cedar Creek 164501.71
END DESCRIPTION:
XS GIS Cut Line= 6
      1577719.19      6772997.49      1577635.86      6773265.71
      1577695.32      6773495.21      1577805.93      6773641.72
      1577974.32      6773825.68      1578346.66      6774333.24
#Sta/Elev= 30
  4297.6 1937.62  4859.7 1936.21  4918.0 1935.17  4974.2 1936.24  4988.7 1932.76
  5006.2 1931.91  5006.7 1931.41  5013.3 1931.91  5024.0 1932.07  5045.6 1939.50
  5059.7 1939.58  5073.9 1936.34  5088.1 1935.27  5094.9 1936.35  5102.3 1934.98
  5109.1 1934.98  5116.1 1932.18  5123.2 1936.49  5130.0 1936.72  5172.6 1937.15
  5194.2 1934.75  5208.3 1935.85  5253.1 1934.91  5337.3 1936.27  5408.3 1935.27
  5443.9 1936.62  5514.9 1937.10  5558.8 1936.08  5665.4 1936.25  5878.0 1939.90
#Mann=3,-1,0
  4297.6    0.05       0  5006.2    0.05       0  5013.3    0.05       0
Bank Sta=5006.2,5013.3
Exp/Cntr=0.3,0.1

Type RM Length L Ch R = 1,164089,383,383,383
BEGIN DESCRIPTION:
Cedar Creek 164088.9
END DESCRIPTION:
XS GIS Cut Line= 6
      1577487.41      6773031.35      1577323.36      6773229.25
      1577289.50      6773445.40      1577458.71      6773641.72
      1577636.35      6773917.36      1578008.28      6774323.03
#Sta/Elev= 30
  4265.6 1936.08  4463.9 1934.52  4632.7 1933.96  4896.0 1934.58  4931.1 1935.13
  4953.1 1934.75  4973.9 1933.23  4978.0 1932.06  4978.5 1931.56  4984.6 1931.56
  4985.1 1932.06  4988.2 1933.64  5000.6 1934.21  5090.4 1933.64  5198.4 1934.30
  5220.4 1933.74  5226.3 1934.45  5241.5 1934.34  5247.5 1934.86  5277.8 1933.96
  5305.5 1934.43  5349.2 1933.44  5448.5 1933.22  5512.0 1933.92  5540.4 1933.70
  5554.6 1934.31  5618.1 1934.15  5639.7 1934.76  5780.9 1935.21  5878.9 1936.36
#Mann=3,-1,0
  4265.6    0.05       0  4978.0   0.035       0  4985.1    0.05       0
Bank Sta=4978,4985.1
Exp/Cntr=0.3,0.1

Type RM Length L Ch R = 1,163706,365,365,365
BEGIN DESCRIPTION:
Cedar Creek 163705.83
END DESCRIPTION:
XS GIS Cut Line= 5
      1577177.53      6773250.07      1577084.88      6773730.68
      1577316.35      6773973.32      1577618.49      6774262.32
      1577867.67      6774325.62
#Sta/Elev= 30
  4174.2 1933.32  4371.6 1933.49  4641.1 1932.37  4746.6 1932.78  4888.2 1931.42
  4959.0 1932.33  4965.9 1931.65  4969.6 1930.07  4970.1 1929.57  4976.2 1929.57
  4976.7 1930.07  4980.0 1931.58  4987.3 1932.79  5065.1 1931.99  5149.7 1932.47
  5171.1 1931.94  5185.3 1930.72  5199.4 1932.11  5220.5 1932.46  5241.9 1931.80
  5263.0 1932.52  5376.2 1932.44  5516.7 1933.98  5542.1 1934.79  5557.9 1934.35
  5568.3 1935.39  5583.0 1934.15  5599.2 1935.03  5609.5 1934.63  5674.2 1935.50
#Mann=3,-1,0
  4174.2    0.05       0  4969.6   0.035       0  4976.7    0.05       0
Bank Sta=4969.6,4976.7
Exp/Cntr=0.3,0.1

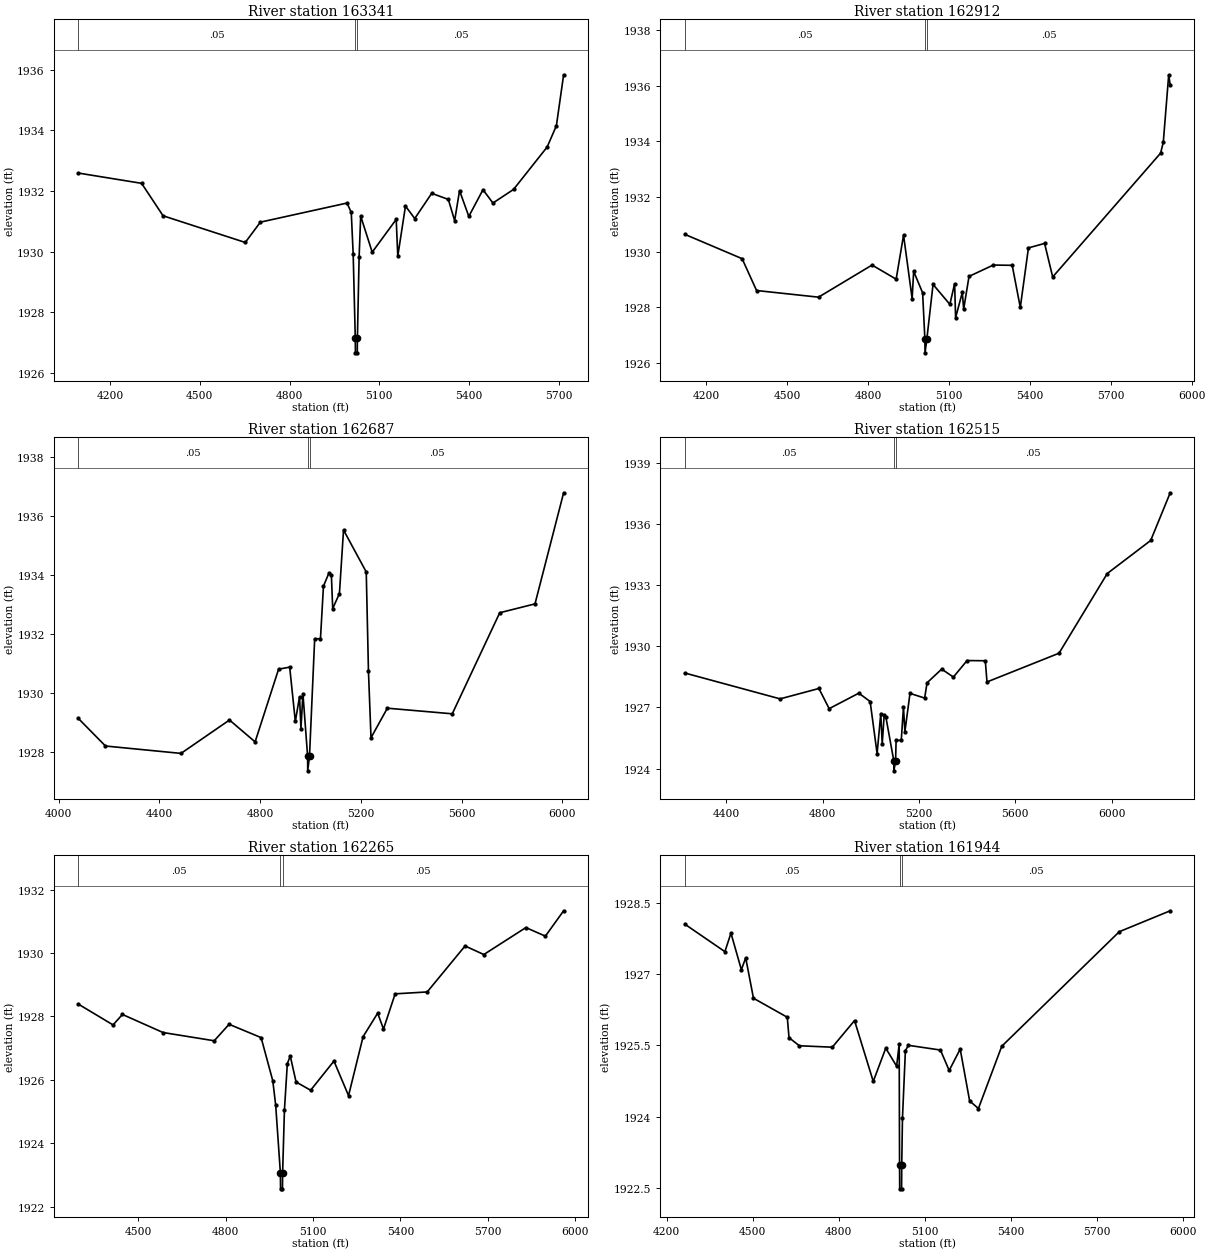
Type RM Length L Ch R = 1,163341,429,429,429
BEGIN DESCRIPTION:
Cedar Creek 163341.12
END DESCRIPTION:
XS GIS Cut Line= 6
      1577062.95      6773388.97      1576911.90      6773665.02
      1576893.67      6773816.06      1577083.71      6774211.17
      1577488.12      6774353.12      1577768.67      6774412.41
#Sta/Elev= 30
  4093.4 1932.59  4305.5 1932.25  4377.3 1931.18  4652.0 1930.30  4702.6 1930.97
  4992.2 1931.60  5006.3 1931.29  5012.7 1929.92  5019.7 1927.16  5020.2 1926.66
  5026.4 1926.66  5026.9 1927.16  5032.5 1929.81  5037.8 1931.17  5076.3 1929.98
  5156.5 1931.06  5161.8 1929.85  5187.5 1931.50  5218.5 1931.09  5275.2 1931.92
  5330.7 1931.72  5351.9 1931.02  5368.2 1932.01  5399.2 1931.16  5446.6 1932.04
  5479.8 1931.60  5548.8 1932.05  5661.2 1933.45  5691.9 1934.15  5716.1 1935.83
#Mann=3,-1,0
  4093.4    0.05       0  5019.7    0.05       0  5026.9    0.05       0
Bank Sta=5019.7,5026.9
Exp/Cntr=0.3,0.1

Type RM Length L Ch R = 1,162912,225,225,225
BEGIN DESCRIPTION:
Cedar Creek 162911.5
END DESCRIPTION:
XS GIS Cut Line= 6
      1576831.17      6773696.26      1576667.93      6774167.16
      1576855.56      6774499.25      1576977.08      6774533.97
      1577346.88      6774518.56      1577770.65      6774508.78
#Sta/Elev= 30
  4120.3 1930.64  4333.1 1929.76  4386.7 1928.61  4616.5 1928.37  4814.9 1929.53
  4904.3 1929.02  4931.7 1930.61  4963.5 1928.32  4969.2 1929.30  5002.4 1928.53
  5010.8 1926.86  5011.3 1926.36  5018.1 1926.86  5041.1 1928.83  5103.5 1928.11
  5121.1 1928.86  5124.7 1927.63  5149.6 1928.54  5154.6 1927.94  5174.5 1929.12
  5264.5 1929.53  5334.6 1929.52  5364.6 1928.00  5394.8 1930.15  5454.7 1930.31
  5484.7 1929.10  5884.8 1933.57  5894.8 1933.96  5914.9 1936.40  5920.5 1936.02
#Mann=3,-1,0
  4120.3    0.05       0  5010.8   0.035       0  5018.1    0.05       0
Bank Sta=5010.8,5018.1
Exp/Cntr=0.3,0.1

Type RM Length L Ch R = 1,162687,172,172,172
BEGIN DESCRIPTION:
Cedar Creek 162687.04
END DESCRIPTION:
XS GIS Cut Line= 6
      1576708.78      6773865.52      1576600.78      6774173.46
      1576827.78      6774714.52      1576951.04      6774719.73
      1576982.29      6774639.87      1577768.68      6774610.33
#Sta/Elev= 30
  4077.1 1929.15  4185.7 1928.21  4485.6 1927.96  4678.1 1929.09  4779.9 1928.35
  4873.1 1930.81  4917.2 1930.88  4939.6 1929.04  4956.3 1929.88  4961.9 1928.80
  4969.8 1929.98  4988.3 1927.87  4988.8 1927.37  4995.9 1927.87  5016.4 1931.84
  5039.4 1931.84  5051.3 1933.62  5072.8 1934.06  5082.7 1934.01  5088.0 1932.86
  5114.7 1933.37  5131.0 1935.52  5221.2 1934.10  5230.0 1930.74  5240.1 1928.49
  5305.0 1929.49  5562.8 1929.30  5751.3 1932.72  5891.3 1933.02  6005.0 1936.78
#Mann=3,-1,0
  4077.1    0.05       0  4988.3   0.035       0  4995.9    0.05       0
Bank Sta=4988.3,4995.9
Exp/Cntr=0.3,0.1

Type RM Length L Ch R = 1,162515,250,250,250
BEGIN DESCRIPTION:
Cedar Creek 162514.96
END DESCRIPTION:
XS GIS Cut Line= 6
      1576648.89      6773909.78      1576561.16      6774265.34
      1576803.47      6774811.75      1576966.67      6774836.05
      1577048.26      6774711.05      1577766.07      6774691.06
#Sta/Elev= 30
  4227.4 1928.69  4623.5 1927.42  4784.6 1927.93  4827.2 1926.94  4950.3 1927.70
  4997.3 1927.29  5026.2 1924.74  5041.5 1926.70  5047.4 1925.21  5055.7 1926.63
  5062.7 1926.53  5095.4 1924.39  5095.9 1923.89  5103.0 1924.39  5105.1 1925.38
  5126.6 1925.39  5135.7 1927.03  5141.6 1925.81  5162.8 1927.69  5223.6 1927.46
  5233.7 1928.21  5294.4 1928.88  5343.0 1928.49  5399.8 1929.30  5475.5 1929.29
  5482.5 1928.25  5781.6 1929.66  5982.0 1933.57  6162.2 1935.19  6243.3 1937.53
#Mann=3,-1,0
  4227.4    0.05       0  5095.4   0.035       0  5103.0    0.05       0
Bank Sta=5095.4,5103
Exp/Cntr=0.3,0.1

Type RM Length L Ch R = 1,162265,321,321,321
BEGIN DESCRIPTION:
Mapping XS 271cfcc5
END DESCRIPTION:
XS GIS Cut Line= 4
      1576607.69      6773912.83      1576459.24      6774379.01
      1576467.05      6775248.80      1576604.63      6775523.95
#Sta/Elev= 30
  4293.7 1928.39  4413.6 1927.73  4445.8 1928.06  4585.2 1927.49  4760.9 1927.23
  4811.9 1927.75  4921.9 1927.33  4961.9 1925.97  4971.9 1925.20  4988.1 1923.06
  4988.6 1922.56  4995.2 1922.56  4995.7 1923.06  5001.9 1925.04  5011.9 1926.51
  5021.9 1926.75  5041.9 1925.93  5091.9 1925.67  5171.9 1926.59  5222.0 1925.50
  5272.0 1927.36  5322.0 1928.10  5342.0 1927.60  5382.0 1928.71  5492.0 1928.77
  5622.0 1930.22  5686.4 1929.95  5830.8 1930.80  5897.8 1930.53  5960.4 1931.33
#Mann=3,-1,0
  4293.7    0.05       0  4988.1   0.035       0  4995.7    0.05       0
Bank Sta=4988.1,4995.7
Exp/Cntr=0.3,0.1

Type RM Length L Ch R = 1,161944,318,318,318
BEGIN DESCRIPTION:
Mapping XS 6bf77e58
END DESCRIPTION:
XS GIS Cut Line= 4
      1576537.38      6773897.22      1576253.51      6774334.74
      1576118.10      6775037.86      1576302.65      6775453.76
#Sta/Elev= 30
  4263.0 1928.05  4403.1 1927.47  4424.2 1927.86  4460.5 1927.09  4475.6 1927.34
  4502.7 1926.49  4620.6 1926.09  4626.6 1925.66  4662.8 1925.49  4777.5 1925.46
  4855.0 1926.02  4920.3 1924.74  4963.9 1925.44  5001.7 1925.06  5010.7 1925.52
  5012.0 1922.98  5012.5 1922.48  5019.1 1922.48  5019.6 1922.98  5022.1 1923.96
  5032.3 1925.38  5042.5 1925.50  5154.5 1925.40  5185.0 1924.97  5223.4 1925.42
  5256.3 1924.33  5286.9 1924.17  5368.3 1925.48  5778.1 1927.89  5955.6 1928.33
#Mann=3,-1,0
  4263.0    0.05       0  5012.0    0.05       0  5019.6    0.05       0
Bank Sta=5012,5019.6
Exp/Cntr=0.3,0.1

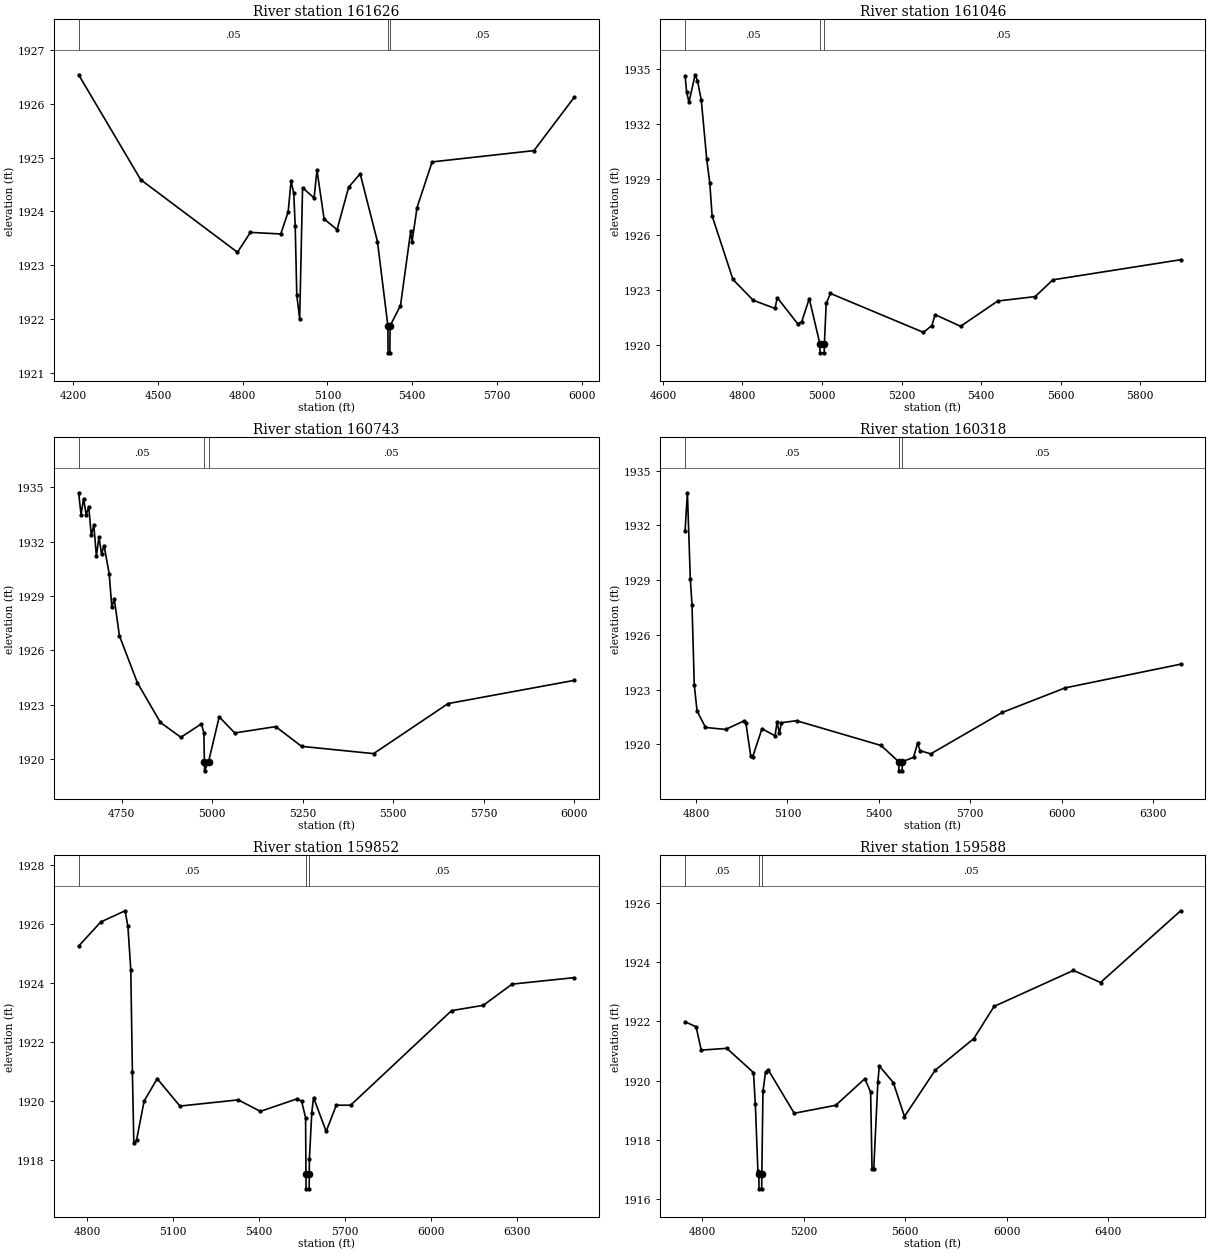
Type RM Length L Ch R = 1,161626,580,580,580
BEGIN DESCRIPTION:
Mapping XS 02f155db
END DESCRIPTION:
XS GIS Cut Line= 4
      1576391.53      6773915.47      1575961.85      6774261.82
      1575836.85      6774889.42      1576050.19      6775409.76
#Sta/Elev= 30
  4219.2 1926.54  4438.9 1924.59  4781.5 1923.24  4827.5 1923.61  4934.8 1923.58
  4960.9 1923.99  4971.1 1924.56  4980.8 1924.34  4985.9 1923.72  4991.5 1922.44
  5001.7 1922.00  5011.9 1924.44  5052.7 1924.25  5062.9 1924.77  5088.1 1923.86
  5134.0 1923.66  5175.1 1924.45  5215.8 1924.70  5277.0 1923.44  5314.0 1921.87
  5314.5 1921.37  5321.1 1921.37  5321.6 1921.87  5358.6 1922.25  5394.6 1923.63
  5399.7 1923.44  5417.1 1924.07  5470.5 1924.92  5831.0 1925.13  5973.4 1926.12
#Mann=3,-1,0
  4219.2    0.05       0  5314.0    0.05       0  5321.6    0.05       0
Bank Sta=5314,5321.6
Exp/Cntr=0.3,0.1

Type RM Length L Ch R = 1,161046,303,303,303
BEGIN DESCRIPTION:
Mapping XS 2d25a07f
END DESCRIPTION:
XS GIS Cut Line= 4
      1575188.44      6774089.96      1575352.47      6774188.90
      1575438.41      6774566.51      1575805.32      6775123.37
#Sta/Elev= 30
  4655.8 1934.62  4659.7 1933.72  4665.5 1933.19  4681.0 1934.67  4686.9 1934.35
  4696.5 1933.30  4710.2 1930.09  4717.9 1928.79  4723.7 1927.02  4776.1 1923.57
  4827.0 1922.44  4881.8 1922.00  4887.5 1922.58  4938.7 1921.17  4949.0 1921.28
  4967.9 1922.53  4994.5 1920.09  4995.0 1919.59  5005.5 1919.59  5006.0 1920.09
  5010.5 1922.27  5021.2 1922.81  5255.0 1920.70  5276.1 1921.07  5284.3 1921.66
  5348.4 1921.03  5441.7 1922.40  5535.8 1922.64  5580.3 1923.55  5901.5 1924.64
#Mann=3,-1,0
  4655.8    0.05       0  4994.5    0.05       0  5006.0    0.05       0
Bank Sta=4994.5,5006
Exp/Cntr=0.3,0.1

Type RM Length L Ch R = 1,160743,425,425,425
BEGIN DESCRIPTION:
Cedar Creek 160743.08
END DESCRIPTION:
XS GIS Cut Line= 3
      1574841.58      6774132.00      1575100.25      6774395.88
      1575742.60      6775161.49
#Sta/Elev= 30
  4630.8 1934.70  4637.5 1933.49  4644.5 1934.38  4651.7 1933.47  4658.7 1933.94
  4665.8 1932.35  4672.8 1932.91  4679.9 1931.21  4686.9 1932.27  4694.1 1931.33
  4701.1 1931.79  4715.2 1930.23  4722.4 1928.42  4729.4 1928.82  4743.5 1926.81
  4793.1 1924.22  4856.7 1922.03  4913.3 1921.21  4969.8 1921.95  4976.8 1921.46
  4978.2 1919.86  4978.7 1919.36  4989.7 1919.86  5019.1 1922.34  5062.0 1921.45
  5175.2 1921.80  5246.7 1920.71  5445.7 1920.31  5651.3 1923.07  5999.7 1924.35
#Mann=3,-1,0
  4630.8    0.05       0  4978.2    0.05       0  4989.7    0.05       0
Bank Sta=4978.2,4989.7
Exp/Cntr=0.3,0.1

Type RM Length L Ch R = 1,160318,466,466,466
BEGIN DESCRIPTION:
Cedar Creek 160317.64
END DESCRIPTION:
XS GIS Cut Line= 4
      1574600.25      6774281.30      1574711.36      6774493.10
      1575292.07      6775200.79      1575762.54      6775243.14
#Sta/Elev= 30
  4763.8 1931.72  4771.4 1933.79  4780.9 1929.08  4786.5 1927.65  4793.9 1923.25
  4803.0 1921.83  4830.7 1920.92  4896.8 1920.81  4957.3 1921.28  4963.3 1921.17
  4979.4 1919.34  4985.9 1919.32  5016.2 1920.85  5059.2 1920.46  5065.7 1921.21
  5073.6 1920.60  5080.1 1921.18  5129.6 1921.29  5407.3 1919.93  5465.3 1919.04
  5465.8 1918.54  5476.4 1918.54  5476.9 1919.04  5513.8 1919.28  5527.1 1920.06
  5535.0 1919.65  5570.2 1919.47  5804.8 1921.74  6011.7 1923.09  6390.8 1924.39
#Mann=3,-1,0
  4763.8    0.05       0  5465.3   0.035       0  5476.9    0.05       0
Bank Sta=5465.3,5476.9
Exp/Cntr=0.3,0.1

Type RM Length L Ch R = 1,159852,264,264,264
BEGIN DESCRIPTION:
Cedar Creek 159851.99
END DESCRIPTION:
XS GIS Cut Line= 5
      1574183.50      6774765.93      1574412.66      6774786.77
      1574730.76      6774835.53      1575297.09      6775251.74
      1575770.17      6775310.82
#Sta/Elev= 30
  4769.5 1925.26  4846.9 1926.08  4931.7 1926.46  4941.7 1925.93  4951.7 1924.46
  4957.4 1920.97  4962.4 1918.57  4971.8 1918.67  4998.3 1920.00  5044.1 1920.76
  5123.4 1919.83  5327.1 1920.04  5404.5 1919.65  5534.1 1920.08  5548.7 1919.99
  5562.5 1919.44  5563.8 1917.52  5564.3 1917.02  5574.9 1917.02  5575.4 1917.52
  5575.8 1918.03  5584.2 1919.61  5590.4 1920.12  5634.4 1918.97  5669.9 1919.86
  5720.0 1919.86  6072.5 1923.07  6183.4 1923.25  6284.2 1923.97  6501.0 1924.19
#Mann=3,-1,0
  4769.5    0.05       0  5563.8    0.05       0  5575.4    0.05       0
Bank Sta=5563.8,5575.4
Exp/Cntr=0.3,0.1

Type RM Length L Ch R = 1,159588,602,602,602
BEGIN DESCRIPTION:
Cedar Creek 159587.54
END DESCRIPTION:
XS GIS Cut Line= 5
      1574092.32      6774953.43      1574355.37      6775000.31
      1574658.84      6775024.32      1575331.37      6775334.58
      1575957.91      6775469.70
#Sta/Elev= 30
  4732.2 1921.99  4775.5 1921.82  4795.9 1921.03  4896.6 1921.09  5001.7 1920.27
  5009.1 1919.19  5019.1 1916.94  5023.0 1916.83  5023.5 1916.33  5034.1 1916.33
  5034.6 1916.83  5039.1 1919.63  5049.2 1920.28  5059.2 1920.37  5162.4 1918.89
  5325.8 1919.16  5440.6 1920.06  5463.5 1919.61  5469.0 1916.99  5475.8 1917.01
  5492.0 1919.95  5497.8 1920.49  5552.9 1919.93  5596.9 1918.78  5718.1 1920.35
  5870.2 1921.42  5950.0 1922.51  6263.0 1923.73  6369.7 1923.32  6685.4 1925.75
#Mann=3,-1,0
  4732.2    0.05       0  5023.0    0.05       0  5034.6    0.05       0
Bank Sta=5023,5034.6
Exp/Cntr=0.3,0.1

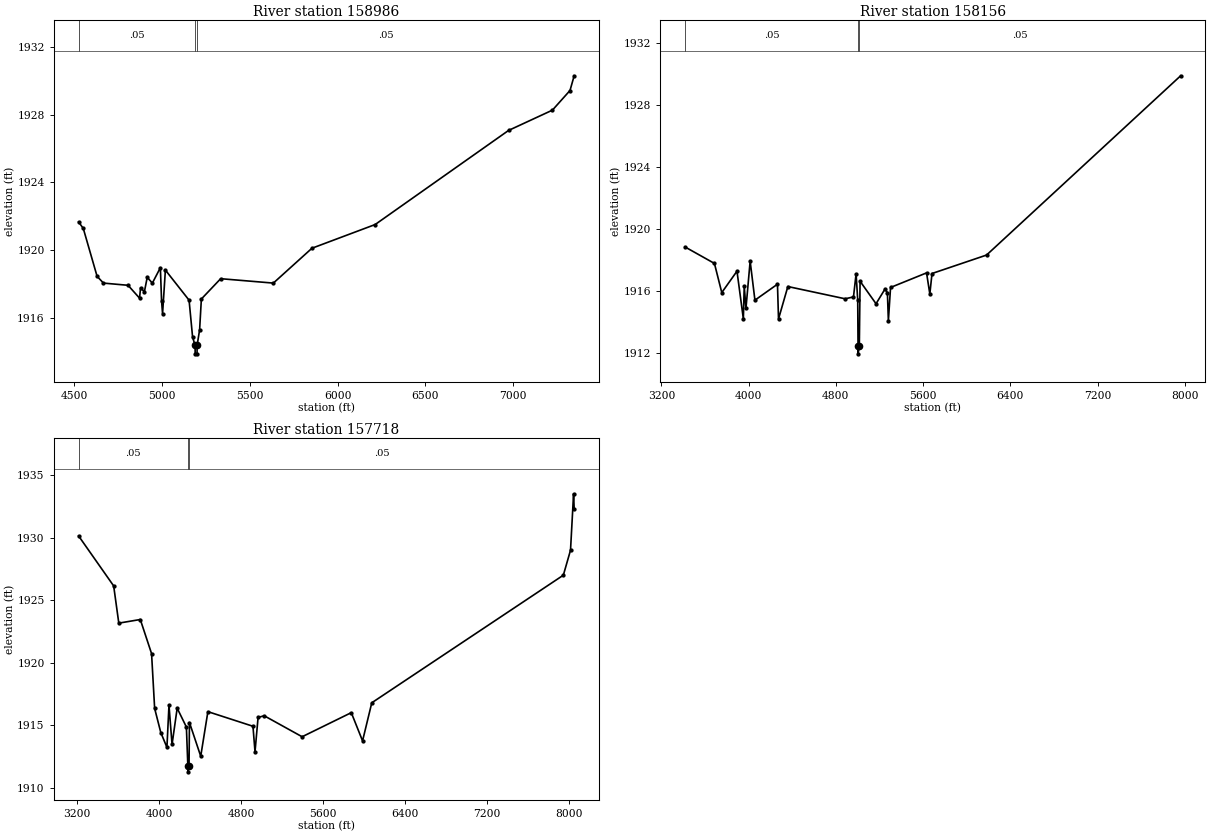
Type RM Length L Ch R = 1,158986,830,830,830
BEGIN DESCRIPTION:
Mapping XS 4c7f0ceb
END DESCRIPTION:
XS GIS Cut Line= 4
      1573922.79      6774975.37      1574019.14      6775126.40
      1574224.87      6775504.01      1576438.84      6775538.28
#Sta/Elev= 30
  4524.2 1921.65  4550.7 1921.27  4629.4 1918.44  4665.7 1918.04  4805.8 1917.91
  4871.3 1917.15  4877.0 1917.76  4898.9 1917.53  4915.0 1918.38  4944.3 1918.04
  4989.9 1918.95  4996.7 1916.99  5002.4 1916.23  5018.5 1918.81  5153.5 1917.03
  5173.5 1914.85  5187.7 1914.36  5188.2 1913.86  5198.8 1913.86  5199.3 1914.36
  5213.5 1915.28  5223.5 1917.10  5333.5 1918.30  5633.6 1918.04  5853.6 1920.10
  6213.6 1921.50  6973.7 1927.06  7223.7 1928.26  7323.8 1929.42  7347.6 1930.29
#Mann=3,-1,0
  4524.2    0.05       0  5187.7    0.05       0  5199.3    0.05       0
Bank Sta=5187.7,5199.3
Exp/Cntr=0.3,0.1

Type RM Length L Ch R = 1,158156,438,438,438
BEGIN DESCRIPTION:
Cedar Creek 159255.76
END DESCRIPTION:
XS GIS Cut Line= 3
      1572054.74      6774918.07      1573766.53      6775633.35
      1576454.03      6775577.79
#Sta/Elev= 30
  3417.9 1918.85  3686.9 1917.79  3754.2 1915.91  3893.6 1917.29  3952.0 1914.22
  3960.1 1916.32  3975.8 1914.89  4014.3 1917.94  4058.1 1915.42  4264.8 1916.45
  4274.4 1914.21  4360.0 1916.30  4884.9 1915.51  4961.8 1915.63  4985.6 1917.12
  5000.5 1915.44  5003.5 1912.46  5004.0 1911.96  5015.2 1912.46  5022.2 1916.64
  5168.5 1915.19  5250.7 1916.14  5272.7 1915.91  5281.6 1914.09  5301.6 1916.24
  5631.7 1917.18  5661.7 1915.82  5681.7 1917.14  6181.8 1918.33  7961.2 1929.89
#Mann=3,-1,0
  3417.9    0.05       0  5003.5    0.05       0  5015.2    0.05       0
Bank Sta=5003.5,5015.2
Exp/Cntr=0.3,0.1

Type RM Length L Ch R = 1,157718,385,385,385
BEGIN DESCRIPTION:
Cedar Creek 159048.17
END DESCRIPTION:
XS GIS Cut Line= 3
      1571422.82      6775813.90      1573532.16      6775793.07
      1576260.68      6775725.38
#Sta/Elev= 30
  3214.0 1930.15  3556.2 1926.15  3606.2 1923.17  3816.2 1923.46  3926.2 1920.73
  3956.2 1916.34  4016.2 1914.41  4076.2 1913.22  4096.2 1916.59  4126.2 1913.45
  4176.2 1916.36  4266.2 1914.85  4280.4 1911.76  4280.9 1911.26  4292.1 1911.76
  4296.2 1915.21  4406.2 1912.51  4476.2 1916.08  4916.3 1914.91  4936.3 1912.87
  4966.3 1915.62  5026.3 1915.75  5396.3 1914.07  5876.4 1916.00  5986.5 1913.74
  6076.5 1916.79  7947.1 1927.01  8017.1 1929.01  8047.1 1933.53  8052.8 1932.30
#Mann=3,-1,0
  3214.0    0.05       0  4280.4   0.035       0  4292.1    0.05       0
Bank Sta=4280.4,4292.1
Exp/Cntr=0.3,0.1