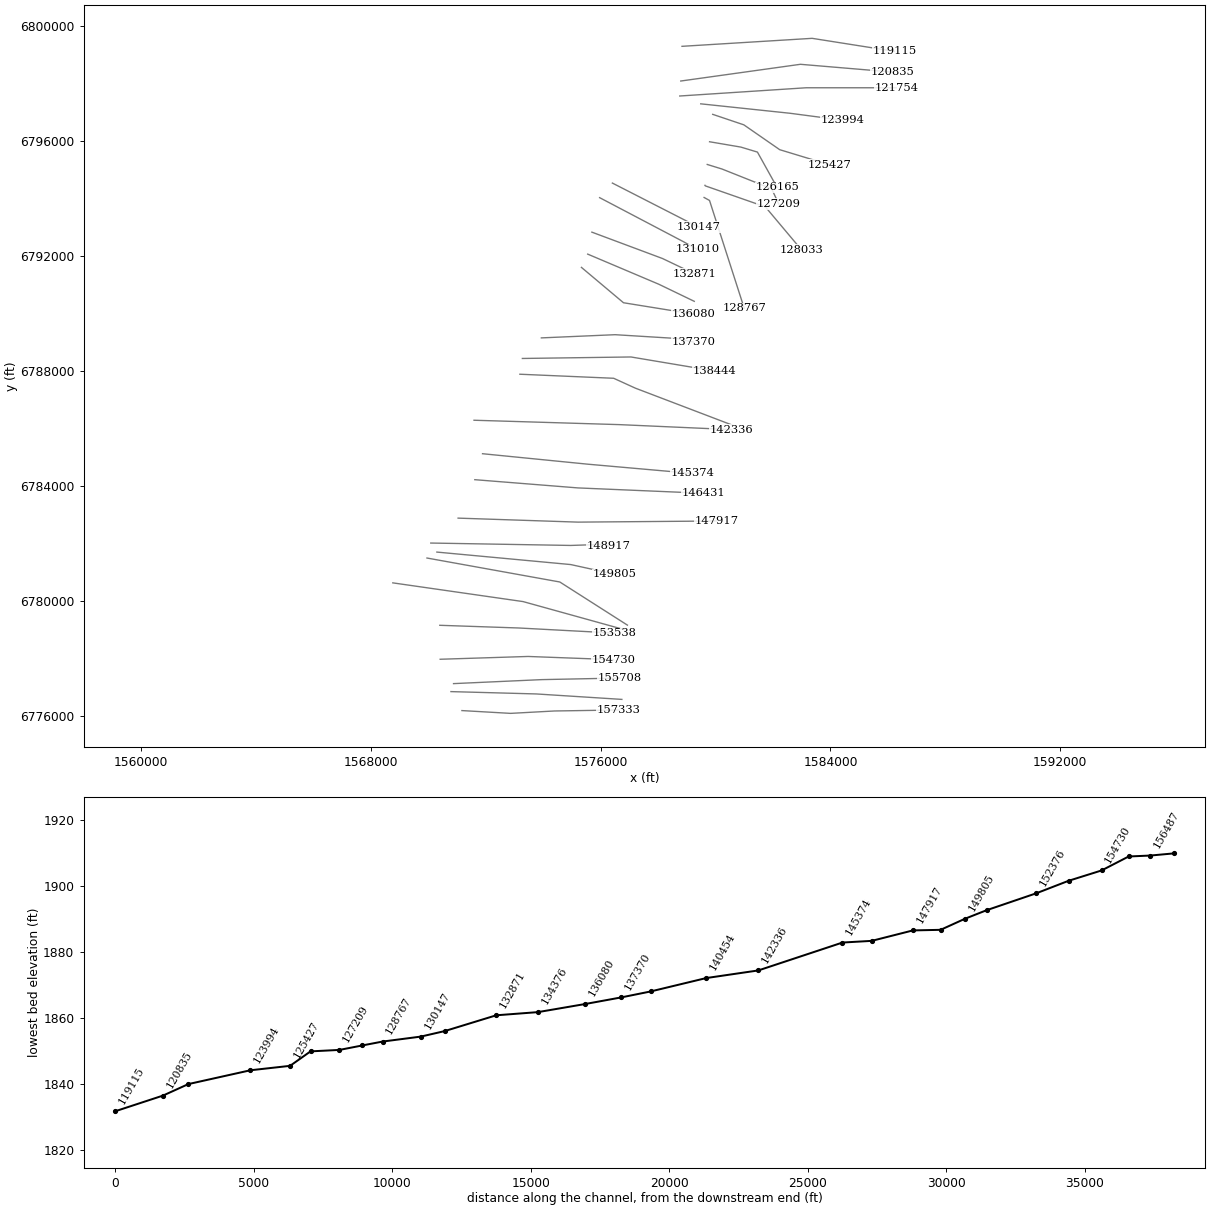
HEC-RAS study Cedar Creek.prj: Cedar Creek Base Level Engineering

--- Cedar Creek.g01 (geometry) --- (continued)

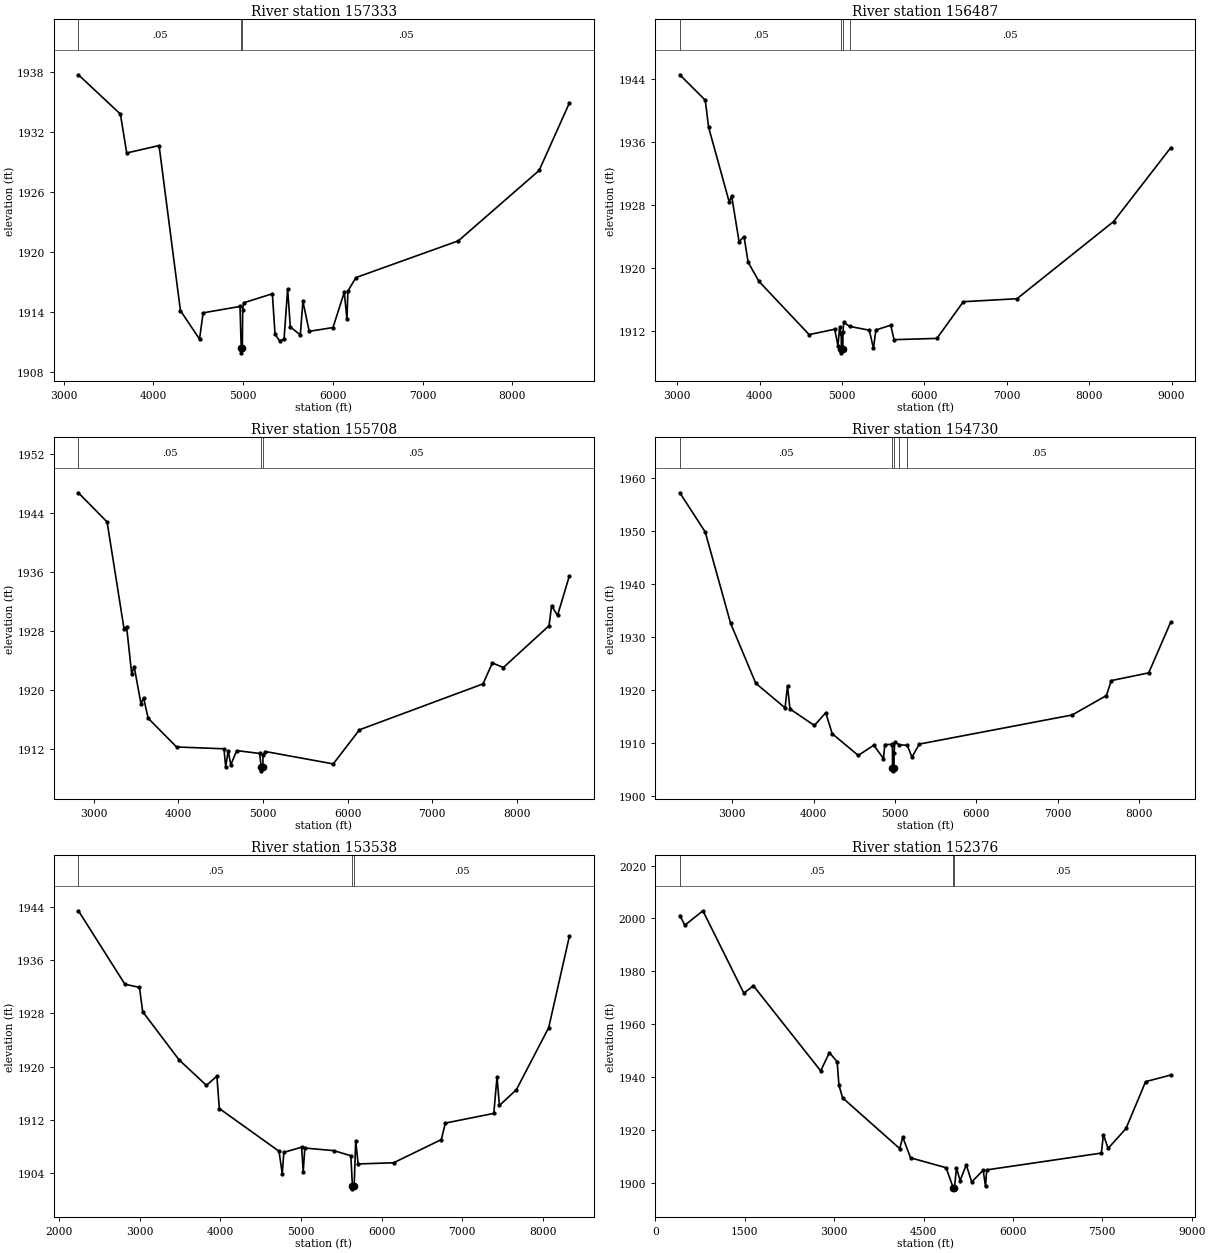
Type RM Length L Ch R = 1,157333,846,846,846
BEGIN DESCRIPTION:
Cedar Creek 158517.36
END DESCRIPTION:
XS GIS Cut Line= 4
      1571167.88      6776178.25      1572862.29      6776081.03
      1574390.07      6776164.36      1576631.56      6776199.06
#Sta/Elev= 30
  3165.7 1937.72  3633.6 1933.79  3703.7 1929.90  4064.3 1930.64  4302.2 1914.14
  4515.0 1911.28  4555.1 1913.91  4965.8 1914.55  4979.5 1910.41  4980.0 1909.91
  4992.0 1910.41  4995.8 1914.18  5005.8 1914.91  5326.3 1915.82  5356.3 1911.76
  5406.4 1911.12  5456.5 1911.26  5496.5 1916.29  5526.6 1912.50  5637.7 1911.70
  5666.8 1915.06  5736.9 1912.06  6001.5 1912.44  6127.5 1915.96  6157.5 1913.25
  6167.5 1916.09  6257.7 1917.44  7398.0 1921.11  8298.1 1928.15  8634.7 1934.89
#Mann=3,-1,0
  3165.7    0.05       0  4979.5   0.035       0  4992.0    0.05       0
Bank Sta=4979.5,4992
Exp/Cntr=0.3,0.1

Type RM Length L Ch R = 1,156487,779,779,779
BEGIN DESCRIPTION:
Cedar Creek 158107.79
END DESCRIPTION:
XS GIS Cut Line= 3
      1570785.87      6776837.97      1573757.64      6776756.63
      1576737.34      6776567.13
#Sta/Elev= 30
  3030.8 1944.50  3340.0 1941.28  3380.1 1937.86  3630.2 1928.39  3660.2 1929.14
  3750.2 1923.34  3810.2 1923.99  3860.2 1920.74  3990.3 1918.33  4600.5 1911.57
  4910.6 1912.25  4950.6 1910.15  4970.7 1912.55  4990.7 1911.68  4991.1 1909.76
  4991.6 1909.26  5010.3 1909.76  5010.7 1911.85  5020.7 1913.11  5092.6 1912.61
  5330.8 1912.13  5380.8 1909.83  5410.8 1912.16  5590.9 1912.76  5630.9 1910.93
  6151.3 1911.09  6472.0 1915.74  7123.3 1916.12  8295.7 1925.90  8989.4 1935.26
#Mann=4,-1,0
  3030.8    0.05       0  4991.1    0.07       0  5010.3    0.05       0
  5092.6    0.05       0
Bank Sta=4991.1,5010.3
Exp/Cntr=0.3,0.1

Type RM Length L Ch R = 1,155708,978,978,978
BEGIN DESCRIPTION:
Cedar Creek 157796.45
END DESCRIPTION:
XS GIS Cut Line= 3
      1570876.15      6777115.75      1573945.62      6777254.64
      1576674.74      6777310.19
#Sta/Elev= 30
  2818.8 1946.71  3158.0 1942.75  3358.2 1928.25  3388.2 1928.56  3448.3 1922.17
  3478.3 1923.11  3558.4 1918.07  3588.4 1918.91  3643.2 1916.12  3978.8 1912.22
  4539.4 1911.97  4559.4 1909.51  4589.5 1911.72  4619.5 1909.77  4689.6 1911.73
  4959.8 1911.34  4980.3 1909.48  4980.8 1908.98  4999.5 1909.48  4999.9 1911.08
  5029.9 1911.60  5830.7 1909.92  6140.8 1914.55  7601.1 1920.78  7711.2 1923.62
  7841.2 1923.00  8381.3 1928.67  8411.3 1931.39  8481.3 1930.06  8621.1 1935.42
#Mann=3,-1,0
  2818.8    0.05       0  4980.3    0.05       0  4999.5    0.05       0
Bank Sta=4980.3,4999.5
Exp/Cntr=0.3,0.1

Type RM Length L Ch R = 1,154730,1192,1192,1192
BEGIN DESCRIPTION:
Cedar Creek 159284.224
END DESCRIPTION:
XS GIS Cut Line= 3
      1570410.93      6777962.97      1573473.40      6778060.19
      1576445.62      6777949.08
#Sta/Elev= 30
  2353.9 1957.25  2666.5 1949.85  2978.3 1932.63  3288.4 1921.28  3648.6 1916.64
  3678.6 1920.81  3708.6 1916.44  4008.8 1913.32  4148.9 1915.71  4228.9 1911.75
  4549.1 1907.66  4739.2 1909.59  4859.2 1907.07  4875.2 1909.72  4959.3 1909.73
  4969.3 1909.61  4969.7 1905.25  4970.2 1904.75  4988.9 1905.25  4989.3 1908.12
  4999.3 1910.22  5052.6 1909.65  5151.6 1909.58  5209.4 1907.33  5299.4 1909.80
  7180.7 1915.30  7601.0 1918.97  7661.1 1921.79  8121.4 1923.25  8392.2 1932.84
#Mann=5,-1,0
  2353.9    0.05       0  4969.7    0.05       0  4988.9    0.05       0
  5052.6    0.12       0  5151.6    0.05       0
Bank Sta=4969.7,4988.9
Exp/Cntr=0.3,0.1

Type RM Length L Ch R = 1,153538,1162,1162,1162
BEGIN DESCRIPTION:
Cedar Creek 153538.49
END DESCRIPTION:
XS GIS Cut Line= 3
      1570398.25      6779143.85      1573148.28      6779050.10
      1576480.85      6778873.06
#Sta/Elev= 30
  2240.6 1943.41  2817.7 1932.37  2997.8 1931.90  3037.8 1928.25  3488.1 1921.02
  3828.3 1917.17  3958.3 1918.55  3988.4 1913.69  4728.8 1907.27  4768.8 1903.89
  4788.8 1907.10  5009.0 1907.88  5029.0 1904.21  5049.0 1907.75  5409.5 1907.36
  5619.8 1906.59  5638.8 1902.12  5639.3 1901.62  5660.9 1902.12  5679.9 1908.85
  5710.0 1905.36  6150.6 1905.54  6741.4 1909.02  6791.5 1911.50  7392.7 1912.96
  7432.4 1918.43  7462.4 1914.15  7672.7 1916.52  8073.3 1925.84  8329.5 1939.55
#Mann=3,-1,0
  2240.6    0.05       0  5638.8   0.035       0  5660.9    0.05       0
Bank Sta=5638.8,5660.9
Exp/Cntr=0.3,0.1

Type RM Length L Ch R = 1,152376,1800,1800,1800
BEGIN DESCRIPTION:
Cedar Creek 152375.75
END DESCRIPTION:
XS GIS Cut Line= 3
      1568761.35      6780619.29      1573296.97      6779968.25
      1576821.71      6778992.17
#Sta/Elev= 30
   409.4 2001.11   493.9 1997.45   797.0 2002.91  1484.0 1971.80  1645.4 1974.57
  2774.1 1942.42  2920.3 1949.35  3049.8 1945.87  3080.1 1937.06  3140.8 1932.24
  4100.5 1913.05  4151.0 1917.39  4282.3 1909.57  4878.4 1905.83  4996.5 1898.35
  4997.0 1897.85  5019.6 1898.35  5052.8 1905.73  5114.0 1900.98  5217.7 1906.91
  5308.4 1900.44  5500.7 1904.88  5540.2 1898.79  5560.2 1905.01  7484.6 1911.36
  7518.9 1918.31  7597.9 1913.13  7898.2 1920.65  8226.9 1938.35  8648.9 1940.85
#Mann=3,-1,0
   409.4    0.05       0  4996.5    0.05       0  5019.6    0.05       0
Bank Sta=4996.5,5019.6
Exp/Cntr=0.3,0.1

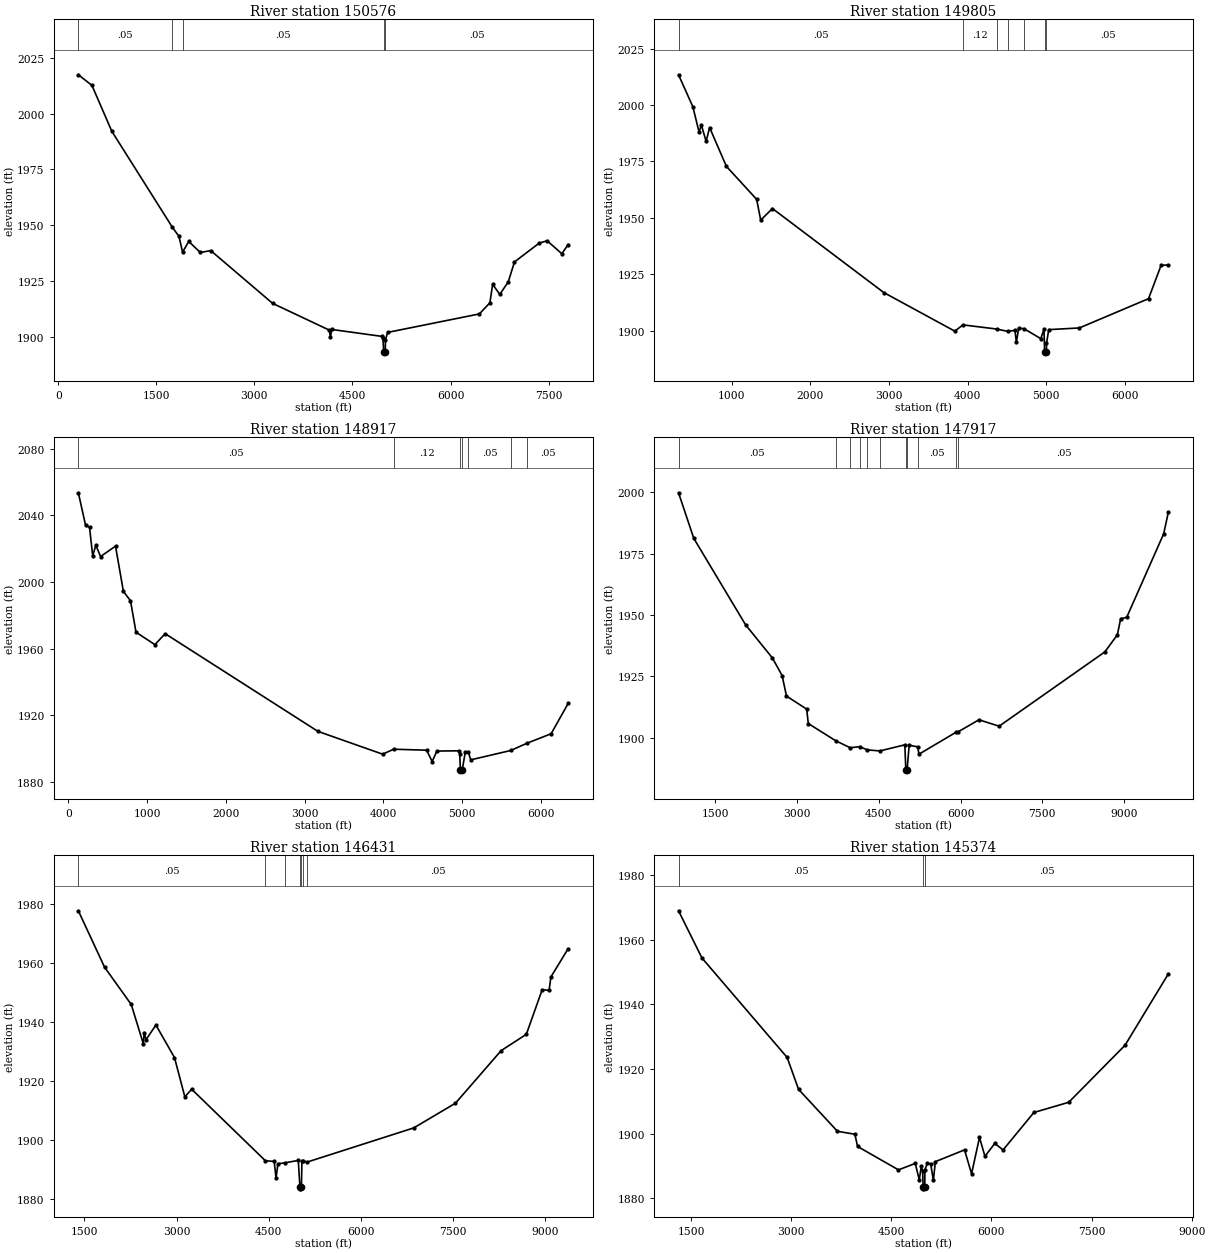
Type RM Length L Ch R = 1,150576,771,771,771
BEGIN DESCRIPTION:
Cedar Creek 150576.33
END DESCRIPTION:
XS GIS Cut Line= 3
      1569951.07      6781483.00      1574576.05      6780649.67
      1576930.14      6779149.72
#Sta/Elev= 30
   308.2 2017.39   515.4 2012.66   820.5 1992.04  1741.2 1949.23  1846.5 1944.95
  1902.1 1937.87  1996.9 1942.65  2173.0 1937.72  2333.8 1938.54  3279.2 1914.89
  4145.5 1902.90  4163.2 1899.79  4183.5 1903.19  4945.6 1900.11  4965.9 1899.33
  4978.4 1893.21  4978.9 1892.71  5001.9 1893.21  5004.6 1898.41  5037.4 1901.87
  6441.2 1910.16  6601.6 1915.13  6643.9 1923.44  6753.1 1918.90  6883.4 1924.58
  6977.4 1933.47  7354.2 1941.87  7477.6 1942.97  7701.9 1937.15  7799.0 1941.26
#Mann=5,-1,0
   308.2    0.05       0  1741.2    0.12       0  1902.1    0.05       0
  4978.4    0.05       0  5001.9    0.05       0
Bank Sta=4978.4,5001.9
Exp/Cntr=0.3,0.1

Type RM Length L Ch R = 1,149805,888,888,888
BEGIN DESCRIPTION:
Cedar Creek 149804.84
END DESCRIPTION:
XS GIS Cut Line= 3
      1570295.48      6781689.60      1574956.96      6781255.57
      1576471.43      6780923.47
#Sta/Elev= 30
   321.1 2013.41   503.3 1999.25   581.7 1988.12   612.5 1991.03   672.1 1983.93
   716.6 1990.02   929.9 1972.82  1314.9 1958.21  1366.6 1948.98  1515.8 1954.13
  2931.9 1916.90  3835.8 1899.78  3940.2 1902.55  4369.5 1900.71  4511.8 1899.66
  4601.6 1900.15  4619.1 1894.90  4649.3 1901.09  4715.9 1900.87  4930.5 1896.45
  4970.6 1900.60  4978.9 1890.66  4979.4 1890.16  5002.5 1890.66  5002.7 1894.34
  5031.5 1900.45  5420.5 1901.19  6300.9 1914.17  6460.8 1928.95  6553.2 1929.12
#Mann=7,-1,0
   321.1    0.05       0  3940.2    0.12       0  4369.5    0.05       0
  4511.8    0.12       0  4715.9    0.05       0  4978.9    0.05       0
  5002.5    0.05       0
Bank Sta=4978.9,5002.5
Exp/Cntr=0.3,0.1

Type RM Length L Ch R = 1,148917,1000,1000,1000
BEGIN DESCRIPTION:
Cedar Creek 148916.62
END DESCRIPTION:
XS GIS Cut Line= 4
      1570082.95      6782003.84      1574957.99      6781920.51
      1576160.57      6781960.19      1576281.01      6781887.25
#Sta/Elev= 30
   127.7 2053.52   219.8 2033.96   269.8 2032.74   309.8 2015.71   349.8 2022.03
   409.8 2015.29   599.8 2021.53   699.8 1994.37   789.8 1988.79   859.9 1969.91
  1099.9 1962.45  1229.9 1969.04  3170.2 1910.44  3990.3 1896.79  4133.5 1899.75
  4550.4 1899.15  4620.4 1892.36  4680.4 1898.65  4960.5 1898.79  4970.5 1897.08
  4978.7 1887.28  4979.2 1886.78  5002.3 1887.28  5040.5 1897.87  5077.5 1898.27
  5110.5 1893.38  5618.3 1898.98  5823.7 1903.32  6131.1 1909.03  6347.5 1927.19
#Mann=7,-1,0
   127.7    0.05       0  4133.5    0.12       0  4978.7    0.07       0
  5002.3    0.12       0  5077.5    0.05       0  5618.3    0.12       0
  5823.7    0.05       0
Bank Sta=4978.7,5002.3
Exp/Cntr=0.3,0.1

Type RM Length L Ch R = 1,147917,1486,1486,1486
BEGIN DESCRIPTION:
Cedar Creek 147917.02
END DESCRIPTION:
XS GIS Cut Line= 3
      1571035.07      6782870.30      1575207.45      6782731.26
      1580020.29      6782770.33
#Sta/Elev= 30
   825.3 1999.72  1105.4 1981.17  2055.9 1946.00  2548.5 1932.50  2726.3 1925.34
  2806.3 1917.00  3176.5 1911.71  3206.6 1905.83  3713.5 1898.79  3976.1 1895.99
  4154.0 1896.44  4285.7 1895.13  4518.5 1894.70  4977.5 1897.18  4995.7 1887.10
  4996.2 1886.60  5019.4 1887.10  5057.5 1897.03  5212.5 1896.36  5237.6 1893.38
  5914.7 1902.27  5961.0 1902.53  6337.6 1907.37  6707.6 1904.76  8647.7 1934.98
  8877.7 1941.94  8937.7 1948.47  9047.7 1949.00  9727.7 1983.06  9813.0 1991.86
#Mann=11,-1,0
   825.3    0.05       0  3713.5    0.12       0  3976.1    0.05       0
  4154.0    0.12       0  4285.7    0.05       0  4518.5    0.12       0
  4995.7    0.07       0  5019.4    0.12       0  5212.5    0.05       0
  5914.7    0.12       0  5961.0    0.05       0
Bank Sta=4995.7,5019.4
Exp/Cntr=0.3,0.1

Type RM Length L Ch R = 1,146431,1057,1057,1057
BEGIN DESCRIPTION:
Cedar Creek 146430.52
END DESCRIPTION:
XS GIS Cut Line= 3
      1571616.64      6784207.11      1575210.41      6783920.65
      1579575.60      6783735.18
#Sta/Elev= 30
  1400.6 1977.55  1827.6 1958.45  2261.7 1945.84  2458.2 1932.56  2472.4 1936.34
  2502.4 1933.90  2663.0 1938.89  2965.7 1927.87  3134.4 1914.57  3244.8 1917.17
  4447.0 1892.92  4589.0 1892.73  4619.1 1887.02  4649.2 1891.92  4772.8 1892.28
  4980.7 1893.06  5008.5 1883.94  5009.0 1883.44  5032.3 1883.94  5040.4 1892.76
  5049.8 1892.95  5122.1 1892.48  6862.0 1904.07  7539.6 1912.42  8283.3 1930.21
  8693.7 1935.74  8952.0 1950.85  9064.0 1950.61  9094.0 1955.18  9374.9 1964.73
#Mann=7,-1,0
  1400.6    0.05       0  4447.0    0.12       0  4772.8    0.05       0
  5008.5    0.05       0  5032.3    0.05       0  5049.8    0.12       0
  5122.1    0.05       0
Bank Sta=5008.5,5032.3
Exp/Cntr=0.3,0.1

Type RM Length L Ch R = 1,145374,3038,3038,3038
BEGIN DESCRIPTION:
Cedar Creek 145373.5
END DESCRIPTION:
XS GIS Cut Line= 3
      1571885.80      6785109.88      1575557.64      6784745.30
      1579191.81      6784424.57
#Sta/Elev= 30
  1312.6 1969.00  1663.5 1954.39  2939.8 1923.60  3110.6 1913.73  3693.5 1900.74
  3954.7 1899.83  3994.9 1896.04  4607.9 1888.80  4859.2 1890.80  4919.5 1885.68
  4949.6 1890.04  4969.7 1888.38  4977.3 1883.43  4977.8 1882.93  5002.2 1883.43
  5002.5 1888.76  5040.0 1890.81  5090.2 1890.67  5130.4 1885.55  5160.5 1891.35
  5597.3 1894.99  5702.6 1887.60  5821.5 1898.83  5903.3 1893.00  6050.7 1897.00
  6174.4 1894.96  6636.2 1906.56  7158.2 1909.72  8001.5 1927.37  8650.8 1949.47
#Mann=3,-1,0
  1312.6    0.05       0  4977.3    0.05       0  5002.2    0.05       0
Bank Sta=4977.3,5002.2
Exp/Cntr=0.3,0.1

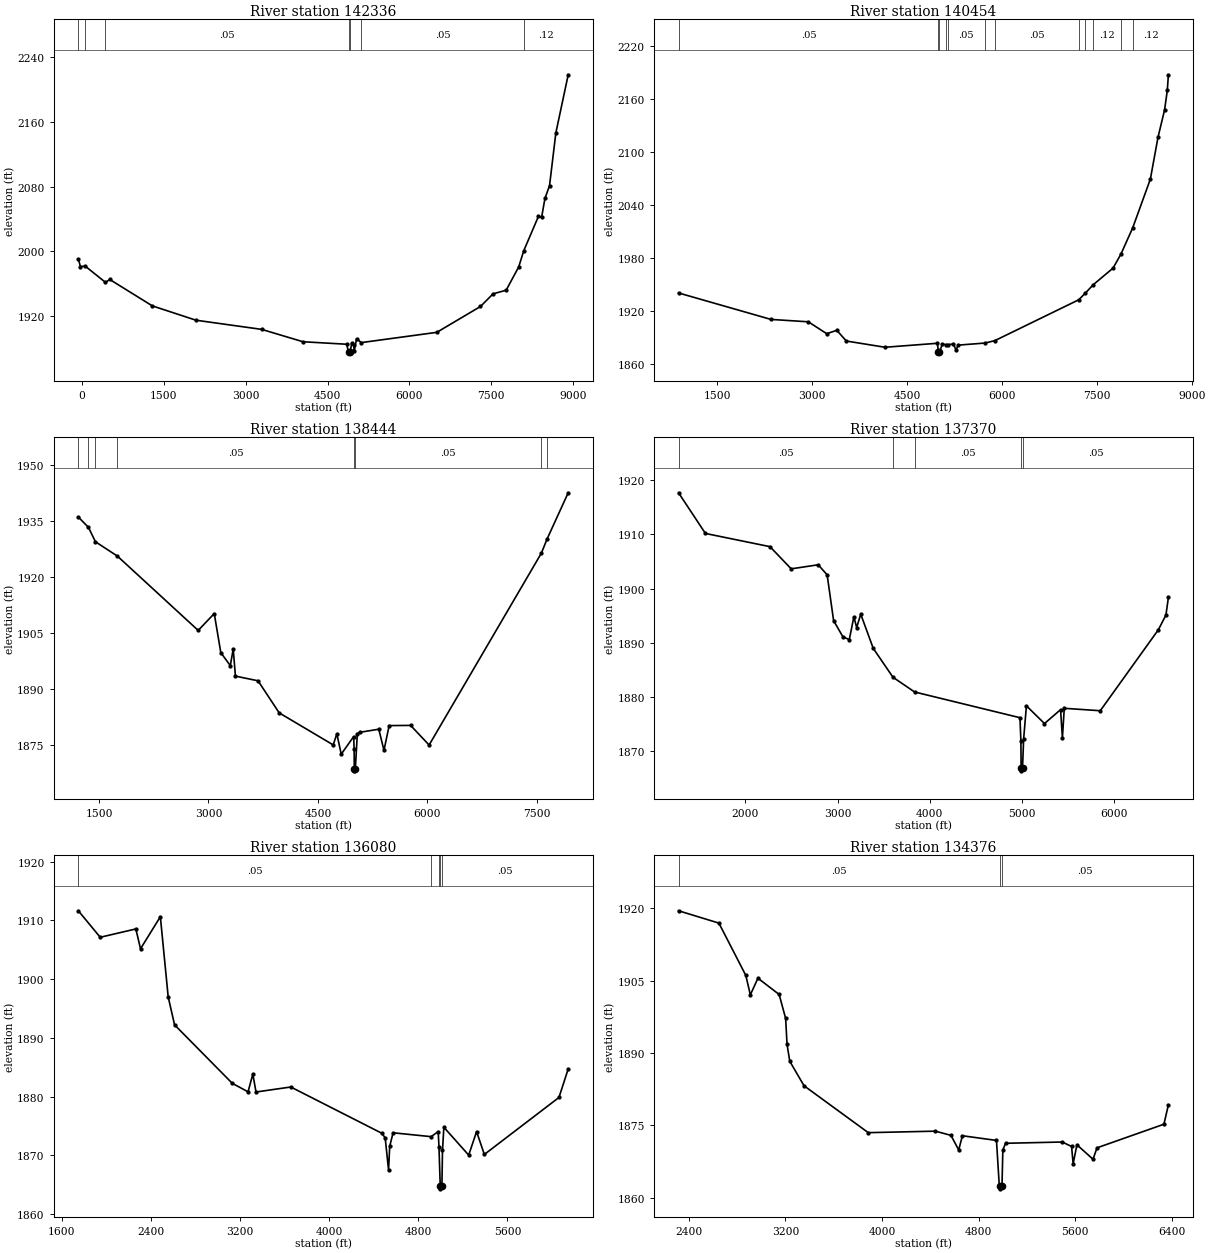
Type RM Length L Ch R = 1,142336,1882,1882,1882
BEGIN DESCRIPTION:
Cedar Creek 142239.73
END DESCRIPTION:
XS GIS Cut Line= 3
      1571589.47      6786274.13      1576658.91      6786121.35
      1580560.81      6785947.78
#Sta/Elev= 30
   -68.0 1990.03   -29.1 1981.10    57.7 1981.62   429.3 1961.55   507.8 1965.12
  1288.1 1932.50  2088.5 1914.79  3291.5 1903.48  4049.4 1888.19  4849.8 1885.12
  4885.4 1874.99  4885.9 1874.49  4914.2 1874.99  4939.8 1886.07  4979.8 1883.65
  4989.8 1877.11  5029.9 1891.90  5119.9 1887.16  6501.3 1899.82  7302.1 1931.77
  7532.3 1947.39  7772.6 1951.89  8002.8 1980.69  8094.7 2000.58  8363.1 2042.95
  8423.2 2042.28  8483.3 2065.18  8567.6 2081.12  8683.5 2146.31  8909.5 2218.04
#Mann=7,-1,0
   -68.0    0.05       0    57.7    0.12       0   429.3    0.05       0
  4885.4    0.07       0  4914.2    0.05       0  5119.9    0.05       0
  8094.7    0.12       0
Bank Sta=4885.4,4914.2
Exp/Cntr=0.3,0.1

Type RM Length L Ch R = 1,140454,2010,2010,2010
BEGIN DESCRIPTION:
Cedar Creek 140454.2
END DESCRIPTION:
XS GIS Cut Line= 4
      1573186.07      6787873.99      1576451.73      6787733.37
      1577206.94      6787389.62      1580611.29      6786093.47
#Sta/Elev= 30
   891.1 1939.98  2351.4 1910.03  2941.9 1907.32  3232.2 1893.88  3392.4 1897.66
  3542.5 1885.56  4153.1 1878.50  4981.7 1883.00  4998.4 1872.68  4998.7 1872.18
  5012.8 1872.68  5060.7 1882.18  5112.2 1881.41  5141.4 1881.35  5236.0 1882.19
  5276.4 1875.13  5308.5 1880.91  5733.3 1883.26  5889.3 1885.99  7216.2 1932.29
  7317.6 1939.66  7445.7 1949.40  7757.9 1968.11  7881.9 1983.95  8068.2 2013.73
  8347.3 2068.90  8467.7 2116.17  8572.1 2147.34  8614.9 2169.29  8632.3 2187.05
#Mann=12,-1,0
   891.1    0.05       0  4998.4    0.05       0  5012.8    0.05       0
  5112.2    0.12       0  5141.4    0.05       0  5733.3    0.12       0
  5889.3    0.05       0  7216.2   0.075       0  7317.6    0.05       0
  7445.7    0.12       0  7881.9    0.05       0  8068.2    0.12       0
Bank Sta=4998.4,5012.8
Exp/Cntr=0.3,0.1

Type RM Length L Ch R = 1,138444,1074,1074,1074
BEGIN DESCRIPTION:
Cedar Creek 138444.4
END DESCRIPTION:
XS GIS Cut Line= 3
      1573272.82      6788422.06      1577054.09      6788474.14
      1579944.76      6787989.76
#Sta/Elev= 30
  1216.7 1936.16  1355.4 1933.39  1450.9 1929.54  1751.2 1925.70  2859.0 1905.77
  3079.1 1910.29  3169.1 1899.80  3299.1 1896.33  3339.1 1900.76  3369.1 1893.52
  3679.1 1892.26  3969.1 1883.66  4709.2 1875.07  4759.2 1878.03  4819.2 1872.59
  4989.2 1877.30  4996.3 1873.97  4997.5 1868.62  4997.7 1868.12  5012.4 1868.62
  5039.8 1878.08  5070.5 1878.44  5333.9 1879.28  5404.8 1873.61  5475.8 1880.25
  5769.9 1880.30  6023.3 1875.04  7562.0 1926.49  7638.2 1930.20  7929.3 1942.67
#Mann=8,-1,0
  1216.7    0.12       0  1355.4    0.05       0  1450.9    0.12       0
  1751.2    0.05       0  4997.5    0.05       0  5012.4    0.05       0
  7562.0    0.12       0  7638.2    0.05       0
Bank Sta=4997.5,5012.4
Exp/Cntr=0.3,0.1

Type RM Length L Ch R = 1,137370,1290,1290,1290
BEGIN DESCRIPTION:
Mapping XS e2f91981
END DESCRIPTION:
XS GIS Cut Line= 4
      1573933.44      6789137.58      1576502.92      6789248.69
      1578655.70      6789116.75      1579231.03      6788991.98
#Sta/Elev= 30
  1273.6 1917.70  1565.4 1910.18  2266.1 1907.74  2496.3 1903.64  2789.7 1904.39
  2886.7 1902.53  2956.7 1894.07  3056.8 1891.10  3126.9 1890.55  3176.9 1894.78
  3207.0 1892.79  3251.4 1895.25  3387.1 1888.94  3601.3 1883.60  3835.4 1880.88
  4979.7 1876.12  4989.7 1871.88  4992.4 1866.80  4992.7 1866.30  5007.4 1866.80
  5019.8 1872.23  5049.8 1878.32  5245.7 1875.04  5420.5 1877.61  5440.5 1872.38
  5460.6 1877.86  5851.3 1877.41  6482.5 1892.39  6564.4 1895.11  6591.0 1898.35
#Mann=5,-1,0
  1273.6    0.05       0  3601.3    0.12       0  3835.4    0.05       0
  4992.4    0.05       0  5007.4    0.05       0
Bank Sta=4992.4,5007.4
Exp/Cntr=0.3,0.1

Type RM Length L Ch R = 1,136080,1704,1704,1704
BEGIN DESCRIPTION:
Cedar Creek 137377.38
END DESCRIPTION:
XS GIS Cut Line= 3
      1575329.34      6791588.95      1576793.68      6790359.56
      1579246.76      6789963.73
#Sta/Elev= 30
  1748.9 1911.64  1945.2 1907.13  2265.2 1908.55  2306.9 1905.17  2485.0 1910.63
  2555.3 1896.99  2612.5 1892.23  3130.3 1882.28  3272.1 1880.83  3315.0 1883.85
  3343.6 1880.80  3655.8 1881.65  4472.6 1873.78  4503.0 1873.00  4533.4 1867.51
  4543.5 1871.55  4573.9 1873.86  4915.4 1873.20  4979.0 1874.06  4985.8 1871.45
  4997.3 1864.82  4997.5 1864.32  5012.2 1864.82  5017.4 1870.86  5029.7 1874.80
  5252.5 1870.06  5323.4 1874.06  5393.1 1870.17  6062.9 1879.87  6145.7 1884.72
#Mann=5,-1,0
  1748.9    0.05       0  4915.4    0.12       0  4985.8    0.05       0
  4997.3    0.05       0  5012.2    0.05       0
Bank Sta=4997.3,5012.2
Exp/Cntr=0.3,0.1

Type RM Length L Ch R = 1,134376,1505,1505,1505
BEGIN DESCRIPTION:
Cedar Creek 134376.09
END DESCRIPTION:
XS GIS Cut Line= 3
      1575547.23      6792050.50      1578026.37      6791001.90
      1579257.82      6790409.07
#Sta/Elev= 30
  2314.4 1919.48  2648.6 1916.93  2871.9 1906.08  2909.2 1902.06  2972.1 1905.51
  3148.0 1902.14  3201.7 1897.17  3213.2 1891.79  3236.2 1888.28  3354.3 1883.22
  3886.3 1873.51  4442.1 1873.82  4571.4 1872.95  4635.5 1869.93  4666.2 1872.87
  4948.5 1871.90  4972.1 1862.37  4978.1 1862.37  4978.3 1861.87  4994.1 1862.37
  5001.3 1869.91  5024.0 1871.31  5493.2 1871.57  5570.7 1870.65  5583.7 1867.08
  5615.1 1871.00  5748.3 1868.00  5781.6 1870.37  6335.9 1875.26  6372.9 1879.28
#Mann=3,-1,0
  2314.4    0.05       0  4978.1    0.05       0  4994.1    0.05       0
Bank Sta=4978.1,4994.1
Exp/Cntr=0.3,0.1

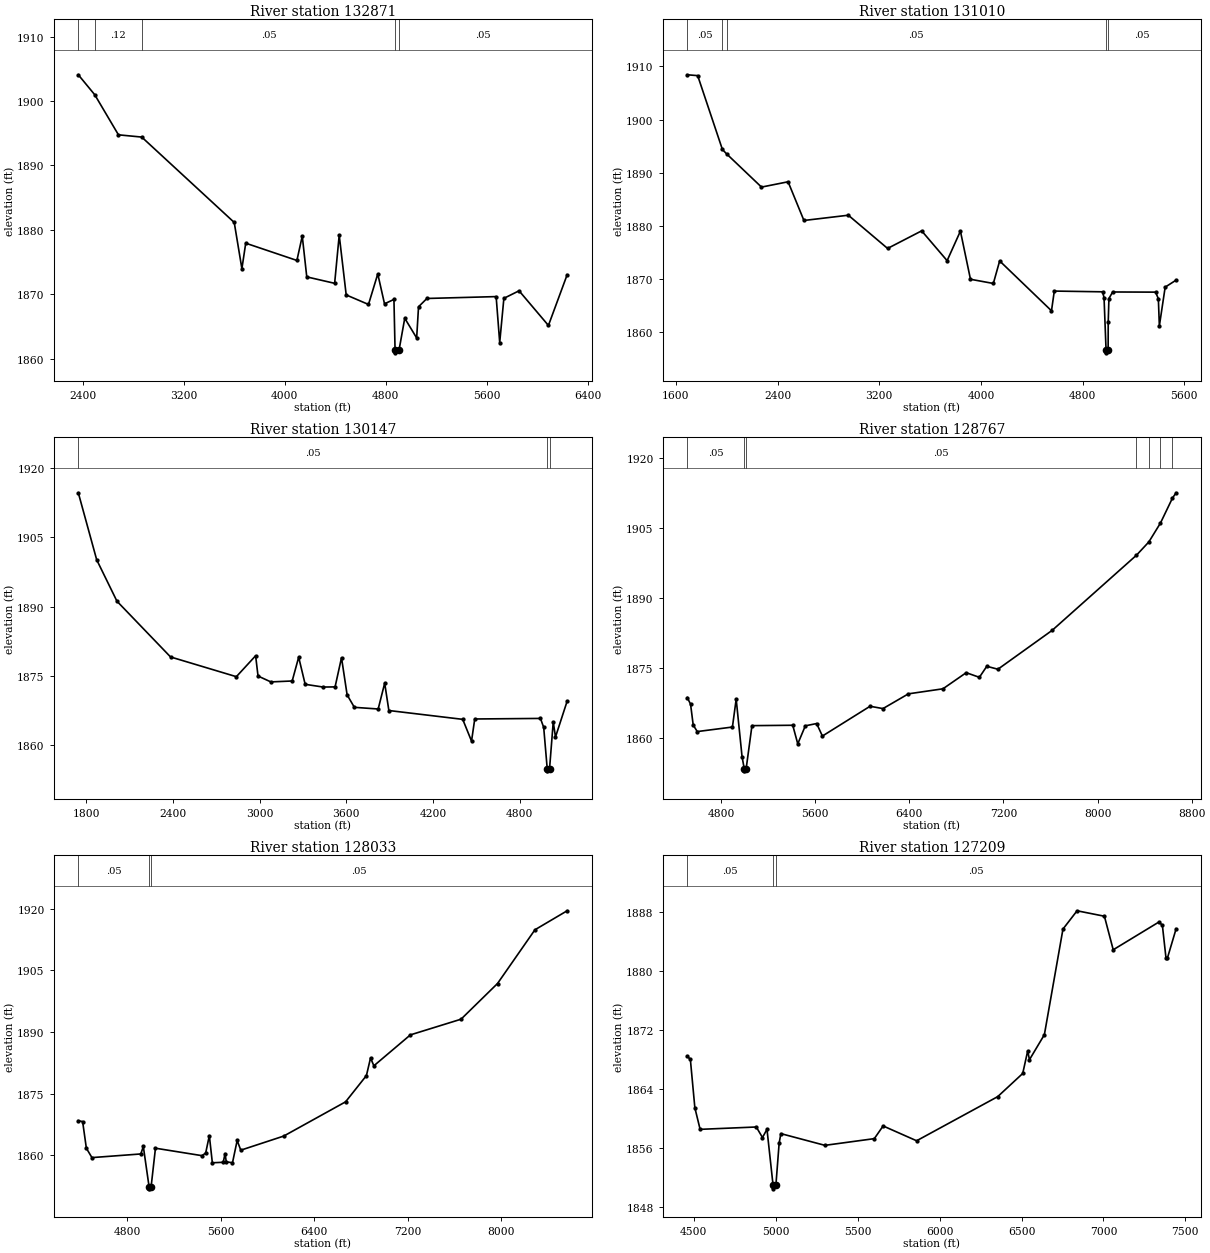
Type RM Length L Ch R = 1,132871,1861,1861,1861
BEGIN DESCRIPTION:
Cedar Creek 132871.05
END DESCRIPTION:
XS GIS Cut Line= 3
      1575692.99      6792814.42      1578151.37      6791897.73
      1579277.27      6791360.80
#Sta/Elev= 30
  2365.8 1904.07  2496.1 1900.97  2683.7 1894.75  2868.2 1894.40  3600.6 1881.15
  3661.3 1873.97  3691.6 1877.93  4096.9 1875.25  4139.3 1879.03  4175.0 1872.70
  4395.7 1871.70  4431.9 1879.17  4487.2 1869.90  4663.7 1868.42  4737.3 1873.16
  4790.6 1868.52  4865.3 1869.20  4874.1 1861.41  4874.6 1860.91  4906.4 1861.41
  4950.9 1866.28  5045.2 1863.22  5060.0 1868.06  5126.5 1869.35  5674.6 1869.64
  5702.8 1862.51  5735.8 1869.37  5856.1 1870.54  6088.6 1865.16  6236.9 1873.03
#Mann=5,-1,0
  2365.8    0.05       0  2496.1    0.12       0  2868.2    0.05       0
  4874.1    0.05       0  4906.4    0.05       0
Bank Sta=4874.1,4906.4
Exp/Cntr=0.3,0.1

Type RM Length L Ch R = 1,131010,863,863,863
BEGIN DESCRIPTION:
Cedar Creek 131009.6
END DESCRIPTION:
XS GIS Cut Line= 3
      1575962.42      6794014.05      1578899.89      6792472.40
      1579359.86      6792213.45
#Sta/Elev= 30
  1690.0 1908.44  1772.0 1908.28  1966.4 1894.39  1999.5 1893.56  2273.9 1887.31
  2483.1 1888.31  2607.7 1881.03  2957.0 1882.02  3265.8 1875.77  3533.8 1879.08
  3734.0 1873.47  3838.6 1879.03  3917.7 1869.97  4097.6 1869.18  4147.3 1873.42
  4555.0 1864.04  4577.1 1867.75  4956.7 1867.61  4968.4 1866.51  4984.3 1856.63
  4984.5 1856.13  5000.6 1856.63  5001.2 1861.86  5006.8 1866.35  5036.3 1867.58
  5374.0 1867.55  5395.6 1866.30  5403.5 1861.20  5449.2 1868.49  5535.3 1869.81
#Mann=5,-1,0
  1690.0    0.05       0  1966.4    0.12       0  1999.5    0.05       0
  4984.3    0.05       0  5000.6    0.05       0
Bank Sta=4984.3,5000.6
Exp/Cntr=0.3,0.1

Type RM Length L Ch R = 1,130147,1380,1380,1380
BEGIN DESCRIPTION:
Cedar Creek 130147.35
END DESCRIPTION:
XS GIS Cut Line= 3
      1576406.81      6794521.03      1579302.67      6793041.84
      1579424.21      6792992.34
#Sta/Elev= 30
  1745.6 1914.62  1872.9 1900.12  2013.1 1891.16  2384.0 1879.10  2839.4 1874.83
  2972.7 1879.36  2989.4 1874.97  3078.2 1873.70  3225.8 1873.90  3270.7 1879.05
  3315.6 1873.18  3439.4 1872.59  3522.6 1872.62  3567.1 1878.94  3605.9 1870.90
  3656.0 1868.20  3820.9 1867.84  3865.9 1873.43  3894.8 1867.51  4405.9 1865.60
  4466.9 1860.89  4489.1 1865.68  4943.8 1865.80  4966.3 1863.86  4990.5 1854.96
  4990.8 1854.46  5006.9 1854.96  5032.3 1865.04  5047.9 1861.78  5128.6 1869.54
#Mann=3,-1,0
  1745.6    0.05       0  4990.5    0.05       0  5006.9    0.05       0
Bank Sta=4990.5,5006.9
Exp/Cntr=0.3,0.1

Type RM Length L Ch R = 1,128767,734,734,734
BEGIN DESCRIPTION:
Cedar Creek 128559.27
END DESCRIPTION:
XS GIS Cut Line= 3
      1579600.37      6794019.96      1579789.38      6793916.23
      1580997.72      6790166.21
#Sta/Elev= 30
  4512.5 1868.66  4540.6 1867.23  4563.1 1862.76  4597.6 1861.37  4896.4 1862.34
  4928.4 1868.31  4978.4 1855.97  4996.6 1853.46  4996.9 1852.96  5013.4 1853.46
  5062.5 1862.64  5409.2 1862.72  5451.9 1858.74  5516.1 1862.60  5612.3 1863.09
  5661.3 1860.41  6066.4 1866.79  6176.1 1866.29  6392.3 1869.45  6686.1 1870.53
  6883.7 1873.98  6995.6 1872.99  7058.7 1875.35  7153.2 1874.72  7615.5 1883.07
  8331.0 1899.14  8436.1 1901.98  8535.0 1906.03  8637.0 1911.38  8668.0 1912.51
#Mann=7,-1,0
  4512.5    0.05       0  4996.6    0.05       0  5013.4    0.05       0
  8331.0    0.12       0  8436.1    0.05       0  8535.0    0.12       0
  8637.0    0.05       0
Bank Sta=4996.6,5013.4
Exp/Cntr=0.3,0.1

Type RM Length L Ch R = 1,128033,824,824,824
BEGIN DESCRIPTION:
Mapping XS 7393c39e
END DESCRIPTION:
XS GIS Cut Line= 4
      1579629.67      6794443.98      1579643.55      6794423.17
      1581733.83      6793694.00      1582983.80      6792207.92
#Sta/Elev= 30
  4381.0 1868.38  4418.1 1868.16  4449.9 1861.68  4497.6 1859.39  4915.9 1860.28
  4937.1 1862.10  4986.4 1852.28  4986.8 1851.78  5003.7 1852.28  5040.9 1861.68
  5439.5 1859.86  5470.6 1860.53  5501.6 1864.75  5527.4 1858.13  5620.6 1858.25
  5636.1 1860.37  5646.4 1858.36  5699.7 1858.14  5739.6 1863.56  5770.6 1861.20
  6138.1 1864.64  6666.9 1872.98  6845.1 1879.38  6880.2 1883.67  6908.8 1881.76
  7221.0 1889.29  7654.1 1893.11  7966.2 1901.81  8286.2 1914.90  8561.7 1919.53
#Mann=3,-1,0
  4381.0    0.05       0  4986.4   0.035       0  5003.7    0.05       0
Bank Sta=4986.4,5003.7
Exp/Cntr=0.3,0.1

Type RM Length L Ch R = 1,127209,1044,1044,1044
BEGIN DESCRIPTION:
Cedar Creek 127208.89
END DESCRIPTION:
XS GIS Cut Line= 4
      1579709.95      6795168.04      1580226.72      6795008.50
      1581952.14      6794322.27      1582201.70      6793791.97
#Sta/Elev= 30
  4459.9 1868.43  4478.9 1867.98  4506.3 1861.42  4538.4 1858.50  4881.2 1858.82
  4919.1 1857.39  4946.5 1858.51  4983.6 1850.93  4983.9 1850.43  5000.9 1850.93
  5020.7 1856.62  5031.2 1857.92  5300.2 1856.33  5601.6 1857.24  5655.4 1858.96
  5859.8 1856.95  6354.9 1862.94  6507.4 1866.08  6537.8 1869.14  6548.6 1867.95
  6639.6 1871.34  6753.1 1885.67  6839.2 1888.15  7006.0 1887.41  7059.8 1882.86
  7337.6 1886.61  7359.7 1886.21  7381.8 1881.76  7390.0 1881.69  7443.7 1885.71
#Mann=3,-1,0
  4459.9    0.05       0  4983.6    0.05       0  5000.9    0.05       0
Bank Sta=4983.6,5000.9
Exp/Cntr=0.3,0.1

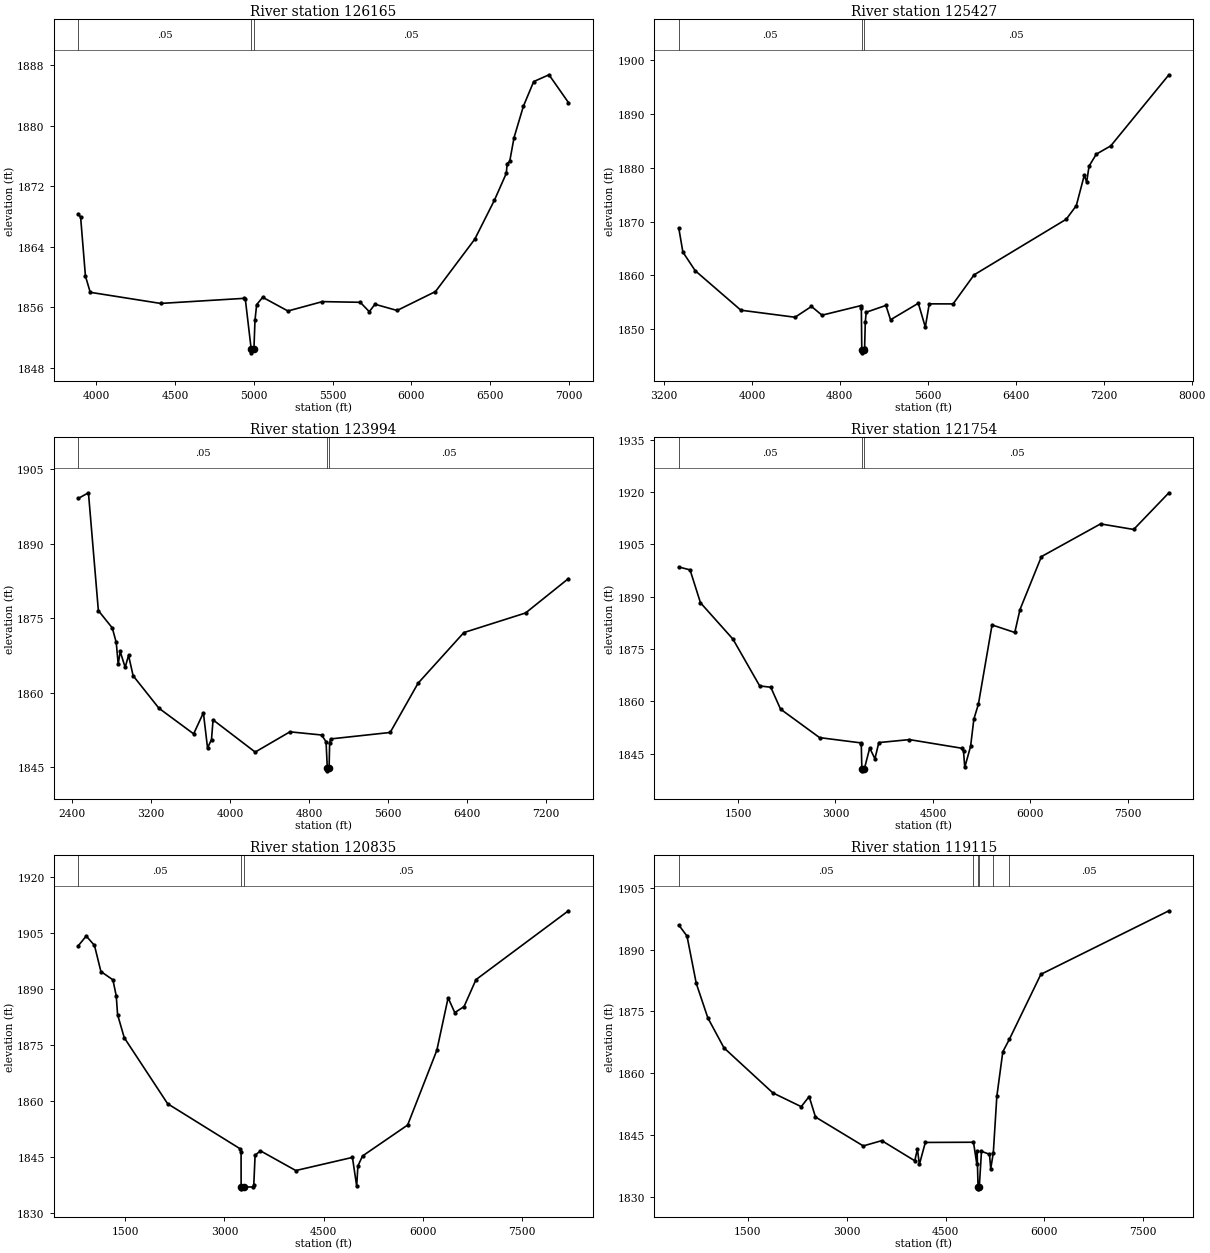
Type RM Length L Ch R = 1,126165,738,738,738
BEGIN DESCRIPTION:
Cedar Creek 126165.22
END DESCRIPTION:
XS GIS Cut Line= 4
      1579790.71      6795957.69      1580879.49      6795772.39
      1581457.35      6795598.31      1582139.63      6794374.38
#Sta/Elev= 30
  3887.5 1868.36  3902.0 1867.89  3932.4 1860.13  3962.9 1857.99  4409.2 1856.52
  4936.7 1857.19  4946.8 1857.07  4984.0 1850.49  4984.4 1849.99  5001.3 1850.49
  5008.1 1854.30  5018.6 1856.36  5057.1 1857.33  5217.0 1855.52  5435.8 1856.76
  5675.9 1856.67  5733.2 1855.43  5769.2 1856.41  5909.8 1855.59  6153.2 1858.09
  6402.4 1865.01  6527.0 1870.16  6602.4 1873.71  6608.1 1875.00  6624.1 1875.30
  6651.6 1878.44  6711.0 1882.59  6776.2 1885.84  6873.3 1886.74  6996.7 1883.07
#Mann=3,-1,0
  3887.5    0.05       0  4984.0    0.05       0  5001.3    0.05       0
Bank Sta=4984,5001.3
Exp/Cntr=0.3,0.1

Type RM Length L Ch R = 1,125427,1433,1433,1433
BEGIN DESCRIPTION:
Mapping XS 89c3d3b6
END DESCRIPTION:
XS GIS Cut Line= 4
      1579900.04      6796910.82      1580983.39      6796546.23
      1582233.39      6795681.65      1583951.03      6795161.15
#Sta/Elev= 30
  3335.3 1868.77  3372.2 1864.35  3484.1 1860.89  3899.7 1853.54  4392.4 1852.23
  4542.0 1854.24  4637.3 1852.61  4989.4 1854.38  4995.5 1853.99  4999.5 1846.11
  4999.9 1845.61  5017.0 1846.11  5025.2 1846.53  5031.3 1851.31  5039.6 1853.16
  5219.1 1854.43  5261.0 1851.76  5513.8 1854.83  5577.3 1850.40  5613.1 1854.72
  5830.0 1854.71  6020.8 1860.11  6858.8 1870.45  6950.8 1872.98  7023.4 1878.65
  7044.8 1877.36  7066.7 1880.33  7132.6 1882.56  7264.2 1884.10  7793.0 1897.32
#Mann=3,-1,0
  3335.3    0.05       0  4999.5    0.05       0  5017.0    0.05       0
Bank Sta=4999.5,5017
Exp/Cntr=0.3,0.1

Type RM Length L Ch R = 1,123994,2240,2240,2240
BEGIN DESCRIPTION:
Cedar Creek 124242.939
END DESCRIPTION:
XS GIS Cut Line= 3
      1579483.41      6797276.26      1582592.77      6796948.14
      1584415.67      6796708.56
#Sta/Elev= 30
  2462.8 1899.17  2565.0 1900.30  2665.5 1876.56  2806.3 1873.07  2846.5 1870.16
  2866.6 1865.74  2886.7 1868.32  2937.0 1865.12  2971.3 1867.54  3017.5 1863.44
  3278.9 1856.89  3630.8 1851.72  3729.5 1855.97  3771.6 1848.88  3811.8 1850.58
  3827.4 1854.54  4254.3 1848.05  4606.2 1852.13  4928.0 1851.49  4972.3 1850.13
  4985.2 1844.77  4985.7 1844.27  5003.1 1844.77  5008.4 1849.80  5018.5 1850.70
  5621.9 1852.00  5904.3 1861.92  6368.3 1872.13  6993.6 1876.08  7428.0 1883.01
#Mann=3,-1,0
  2462.8    0.05       0  4985.2    0.05       0  5003.1    0.05       0
Bank Sta=4985.2,5003.1
Exp/Cntr=0.3,0.1

Type RM Length L Ch R = 1,121754,919,919,919
BEGIN DESCRIPTION:
Cedar Creek 121753.65
END DESCRIPTION:
XS GIS Cut Line= 3
      1578752.66      6797548.59      1583153.75      6797835.05
      1586287.45      6797835.05
#Sta/Elev= 30
   588.6 1898.50   761.3 1897.68   921.6 1888.26  1422.0 1877.83  1833.6 1864.42
  2003.9 1864.05  2154.2 1857.78  2755.5 1849.61  3386.8 1848.11  3396.9 1847.88
  3406.1 1840.59  3407.0 1840.09  3443.7 1840.59  3527.1 1846.63  3607.3 1843.55
  3667.4 1848.19  4138.4 1849.04  4940.1 1846.58  4971.3 1845.64  4990.2 1841.09
  5080.2 1847.14  5130.2 1854.91  5200.2 1859.20  5410.2 1881.90  5760.2 1879.74
  5840.2 1886.30  6170.2 1901.48  7080.2 1910.85  7590.2 1909.26  8132.7 1919.77
#Mann=3,-1,0
   588.6    0.05       0  3406.1    0.05       0  3443.7    0.05       0
Bank Sta=3406.1,3443.7
Exp/Cntr=0.3,0.1

Type RM Length L Ch R = 1,120835,1720,1720,1720
BEGIN DESCRIPTION:
Cedar Creek 120835.38
END DESCRIPTION:
XS GIS Cut Line= 3
      1578787.38      6798069.42      1582954.09      6798651.02
      1586148.57      6798381.92
#Sta/Elev= 30
   790.2 1901.72   909.0 1904.32  1034.1 1901.79  1131.1 1894.80  1312.8 1892.58
  1363.3 1888.27  1383.5 1883.25  1484.5 1877.07  2140.8 1859.39  3241.4 1847.28
  3251.4 1846.50  3252.3 1837.10  3253.2 1836.60  3289.9 1837.10  3433.2 1837.10
  3443.3 1837.53  3463.5 1845.59  3544.3 1846.78  4079.4 1841.50  4935.9 1845.02
  5000.3 1837.31  5018.3 1842.71  5088.2 1845.40  5770.9 1853.69  6212.5 1873.70
  6383.1 1887.76  6483.5 1883.80  6624.0 1885.40  6804.6 1892.63  8203.1 1911.07
#Mann=3,-1,0
   790.2    0.05       0  3252.3    0.05       0  3289.9    0.05       0
Bank Sta=3252.3,3289.9
Exp/Cntr=0.3,0.1

Type RM Length L Ch R = 1,119115,1506,1506,1506
BEGIN DESCRIPTION:
Cedar Creek 119115.46
END DESCRIPTION:
XS GIS Cut Line= 3
      1578830.84      6799276.02      1583362.08      6799553.80
      1586224.81      6799102.71
#Sta/Elev= 30
   451.4 1896.00   575.8 1893.31   716.1 1881.82   891.8 1873.43  1136.8 1866.14
  1878.2 1855.20  2309.0 1851.85  2429.3 1854.31  2525.5 1849.33  3250.8 1842.30
  3531.3 1843.59  4032.3 1838.69  4072.3 1841.52  4102.4 1837.81  4192.6 1843.15
  4923.5 1843.20  4973.5 1837.94  4978.5 1841.00  4992.7 1832.37  4993.2 1831.87
  5011.6 1832.37  5044.7 1841.00  5166.2 1840.26  5185.2 1836.75  5224.3 1840.65
  5277.6 1854.34  5368.7 1865.21  5468.2 1868.23  5945.7 1884.02  7889.2 1899.47
#Mann=6,-1,0
   451.4    0.05       0  4923.5    0.12       0  4992.7    0.07       0
  5011.6    0.12       0  5224.3    0.12       0  5468.2    0.05       0
Bank Sta=4992.7,5011.6
Exp/Cntr=0.3,0.1