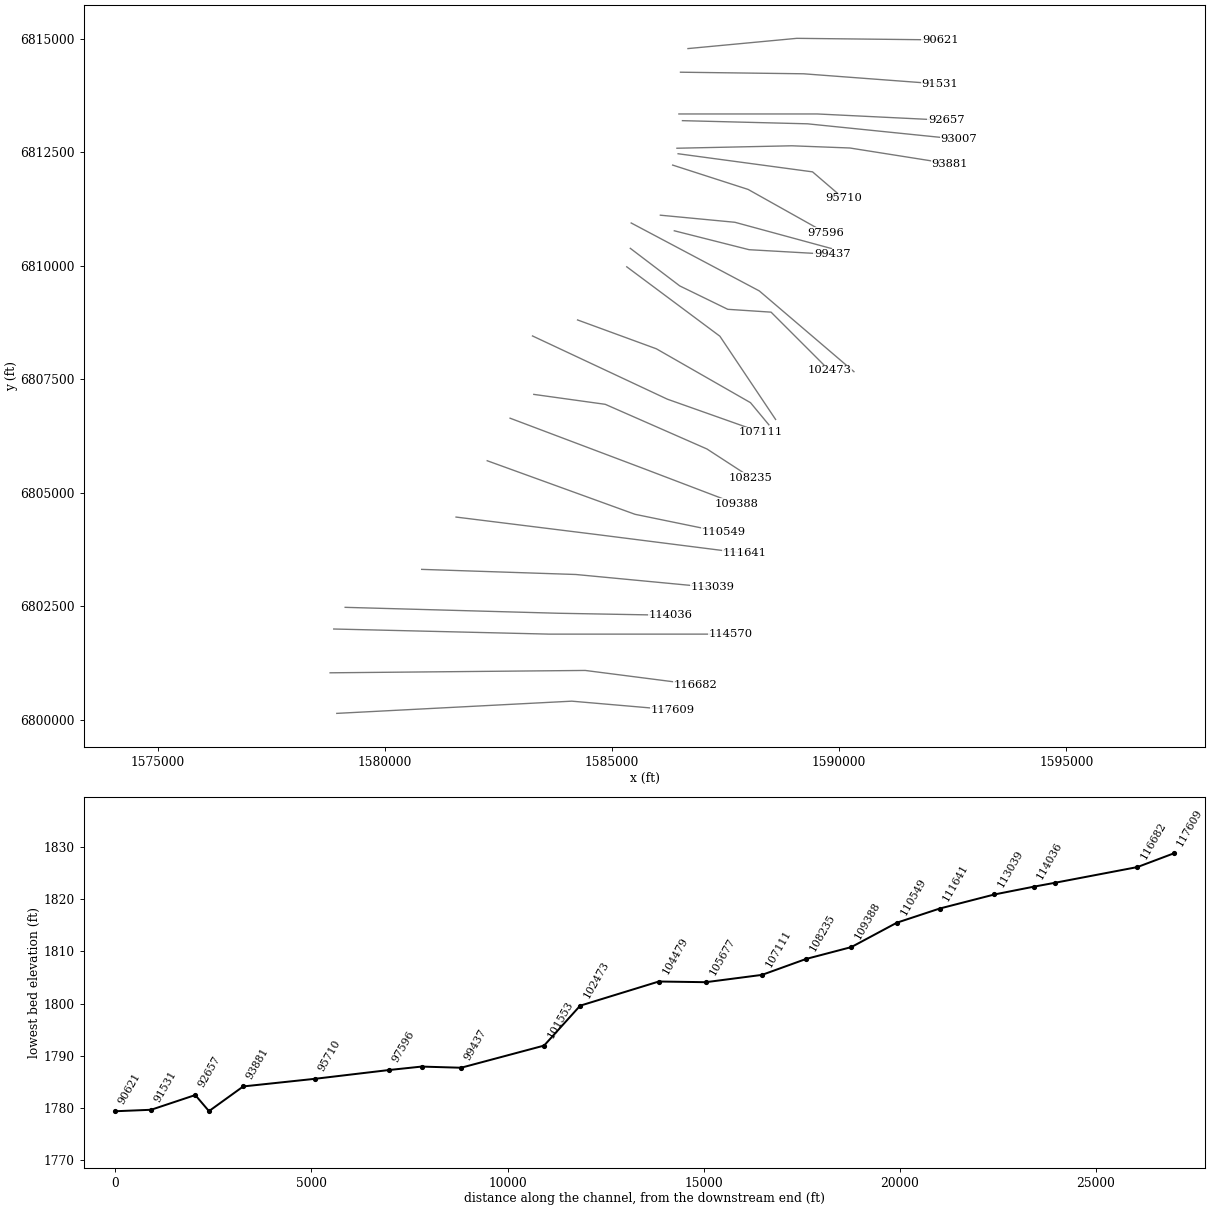
HEC-RAS study Cedar Creek.prj: Cedar Creek Base Level Engineering

--- Cedar Creek.g01 (geometry) --- (continued)

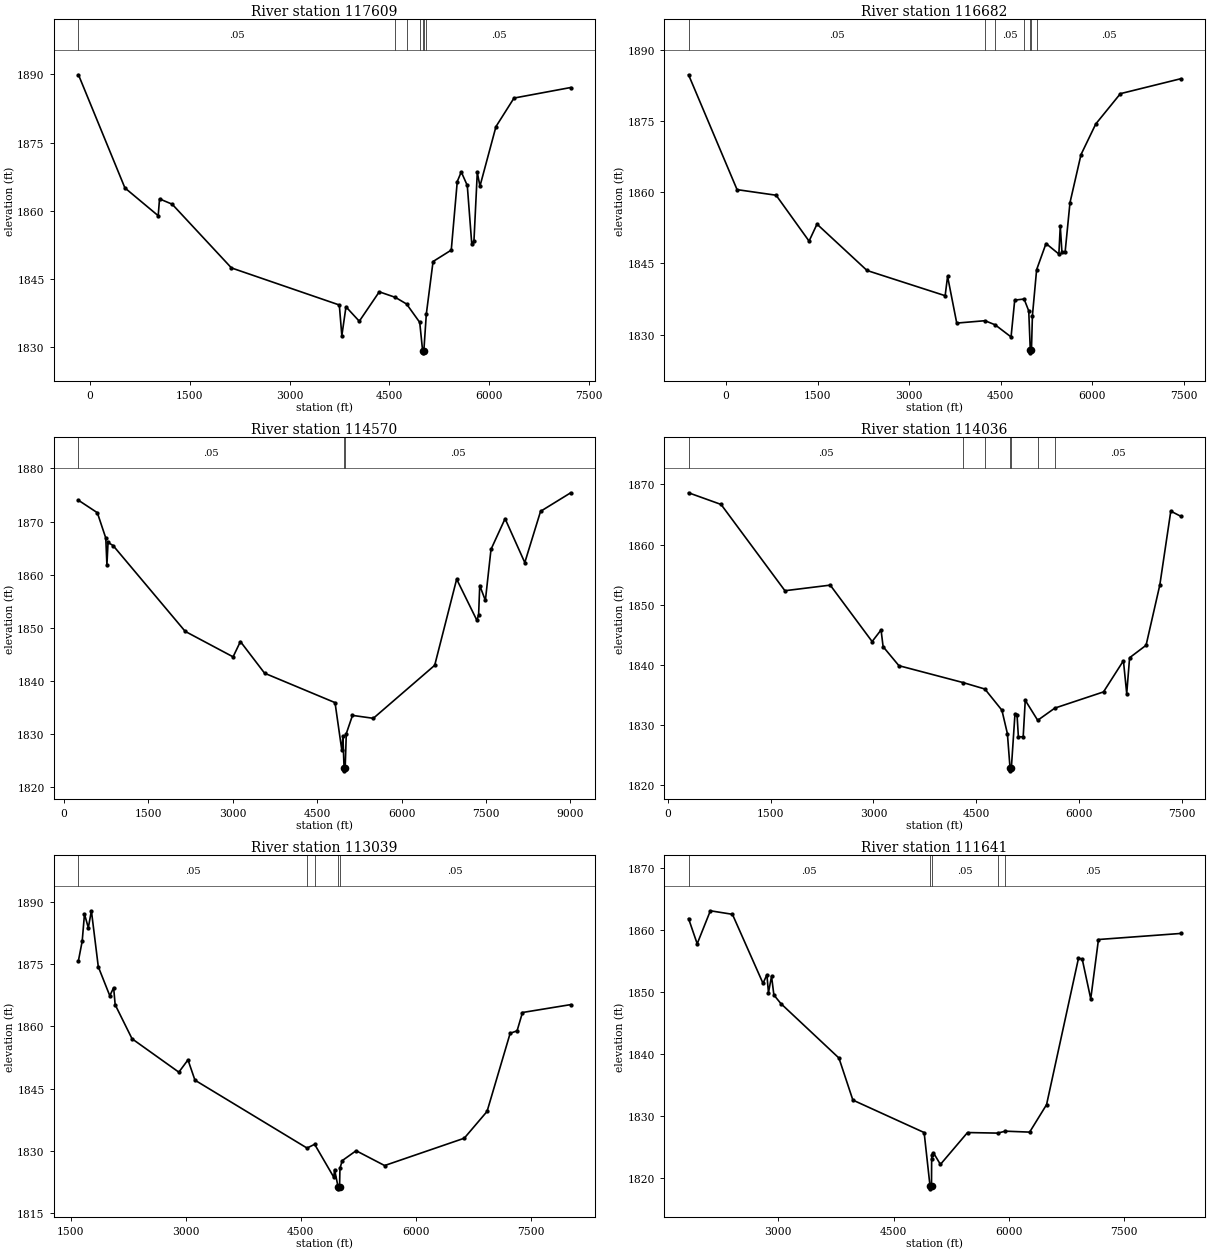
Type RM Length L Ch R = 1,117609,927,927,927
BEGIN DESCRIPTION:
Cedar Creek 117608.61
END DESCRIPTION:
XS GIS Cut Line= 3
      1578937.59      6800137.13      1584111.21      6800406.23
      1586324.77      6800215.26
#Sta/Elev= 30
  -174.5 1889.90   523.9 1865.02  1024.5 1858.91  1044.6 1862.61  1234.8 1861.44
  2126.0 1847.43  3748.2 1839.28  3786.0 1832.53  3848.3 1838.88  4048.6 1835.71
  4349.0 1842.18  4590.3 1840.96  4759.4 1839.50  4957.3 1835.46  5000.5 1829.26
  5001.0 1828.76  5019.5 1829.26  5056.6 1837.30  5157.8 1848.84  5431.5 1851.35
  5521.8 1866.43  5582.0 1868.54  5672.4 1865.56  5739.7 1852.74  5772.7 1853.35
  5822.9 1868.42  5863.1 1865.41  6104.0 1878.51  6375.0 1884.78  7227.9 1887.10
#Mann=7,-1,0
  -174.5    0.05       0  4590.3    0.12       0  4759.4    0.05       0
  4957.3    0.12       0  5000.5    0.07       0  5019.5    0.12       0
  5056.6    0.05       0
Bank Sta=5000.5,5019.5
Exp/Cntr=0.3,0.1

Type RM Length L Ch R = 1,116682,2112,2112,2112
BEGIN DESCRIPTION:
Cedar Creek 116682.23
END DESCRIPTION:
XS GIS Cut Line= 3
      1578790.07      6801031.23      1584406.35      6801083.32
      1586836.92      6800770.81
#Sta/Elev= 30
  -614.7 1884.73   180.3 1860.53   820.3 1859.35  1360.3 1849.68  1490.3 1853.26
  2310.4 1843.49  3590.4 1838.18  3630.4 1842.25  3780.4 1832.41  4243.2 1832.91
  4410.4 1832.04  4670.5 1829.49  4730.5 1837.25  4884.4 1837.48  4960.5 1834.97
  4985.8 1826.64  4986.3 1826.14  5004.8 1826.64  5020.6 1833.97  5089.5 1843.66
  5243.5 1849.17  5454.2 1846.96  5477.1 1852.85  5504.6 1847.32  5556.6 1847.39
  5636.2 1857.78  5817.1 1867.92  6059.1 1874.37  6462.4 1880.75  7452.4 1883.90
#Mann=7,-1,0
  -614.7    0.05       0  4243.2    0.12       0  4410.4    0.05       0
  4884.4    0.12       0  4985.8    0.07       0  5004.8    0.12       0
  5089.5    0.05       0
Bank Sta=4985.8,5004.8
Exp/Cntr=0.3,0.1

Type RM Length L Ch R = 1,114570,534,534,534
BEGIN DESCRIPTION:
Cedar Creek 114569.9
END DESCRIPTION:
XS GIS Cut Line= 3
      1578869.92      6801996.51      1583609.47      6801883.66
      1587610.57      6801883.66
#Sta/Elev= 30
   263.0 1874.01   598.2 1871.67   748.2 1866.90   768.2 1861.87   788.2 1866.08
   878.3 1865.49  2158.6 1849.35  3008.9 1844.56  3138.9 1847.44  3569.0 1841.48
  4819.4 1835.95  4939.4 1827.04  4959.4 1829.61  4980.0 1823.62  4980.5 1823.12
  4999.4 1823.62  5019.4 1830.12  5129.4 1833.55  5499.4 1833.00  6589.4 1842.97
  6979.4 1859.17  7339.4 1851.41  7369.4 1852.51  7389.4 1857.98  7489.4 1855.16
  7589.4 1864.78  7839.4 1870.55  8189.4 1862.29  8469.4 1871.93  9005.0 1875.42
#Mann=3,-1,0
   263.0    0.05       0  4980.0   0.035       0  4999.4    0.05       0
Bank Sta=4980,4999.4
Exp/Cntr=0.3,0.1

Type RM Length L Ch R = 1,114036,997,997,997
BEGIN DESCRIPTION:
Cedar Creek 114035.67
END DESCRIPTION:
XS GIS Cut Line= 3
      1579121.59      6802473.94      1583813.88      6802343.49
      1586290.87      6802298.86
#Sta/Elev= 30
   305.9 1868.60   779.5 1866.66  1709.9 1852.32  2370.1 1853.25  2980.3 1843.87
  3110.4 1845.80  3140.4 1843.02  3370.5 1839.86  4302.7 1837.06  4622.7 1835.98
  4871.1 1832.46  4951.1 1828.56  4989.3 1822.88  4989.8 1822.38  5008.8 1822.88
  5061.1 1831.77  5091.1 1831.74  5111.1 1828.05  5181.2 1828.03  5211.2 1834.11
  5392.5 1830.78  5642.3 1832.81  6351.3 1835.50  6641.4 1840.68  6689.4 1835.22
  6731.4 1841.18  6971.4 1843.25  7171.5 1853.26  7331.5 1865.55  7477.4 1864.69
#Mann=7,-1,0
   305.9    0.05       0  4302.7    0.12       0  4622.7    0.05       0
  4989.3   0.035       0  5008.8    0.05       0  5392.5    0.12       0
  5642.3    0.05       0
Bank Sta=4989.3,5008.8
Exp/Cntr=0.3,0.1

Type RM Length L Ch R = 1,113039,1398,1398,1398
BEGIN DESCRIPTION:
Cedar Creek 113038.63
END DESCRIPTION:
XS GIS Cut Line= 3
      1580806.52      6803310.60      1584200.62      6803197.75
      1587211.36      6802911.43
#Sta/Elev= 30
  1599.3 1875.89  1647.8 1880.53  1677.8 1887.09  1727.8 1883.77  1767.9 1887.87
  1857.9 1874.39  2008.0 1867.40  2058.0 1869.35  2078.0 1865.24  2298.2 1857.04
  2908.5 1849.00  3027.7 1851.96  3118.6 1847.07  4580.4 1830.72  4679.5 1831.63
  4929.6 1823.69  4939.6 1825.53  4985.0 1821.40  4985.5 1820.90  5004.7 1821.40
  5009.7 1825.84  5039.9 1827.70  5220.7 1830.08  5592.3 1826.51  6630.9 1833.09
  6928.3 1839.54  7229.7 1858.36  7320.1 1858.96  7390.4 1863.37  8019.6 1865.27
#Mann=5,-1,0
  1599.3    0.05       0  4580.4    0.12       0  4679.5    0.05       0
  4985.0   0.035       0  5004.7    0.05       0
Bank Sta=4985,5004.7
Exp/Cntr=0.3,0.1

Type RM Length L Ch R = 1,111641,1092,1092,1092
BEGIN DESCRIPTION:
Cedar Creek 111641.37
END DESCRIPTION:
XS GIS Cut Line= 3
      1581563.46      6804463.38      1584705.83      6804072.75
      1587917.66      6803664.76
#Sta/Elev= 30
  1833.6 1861.84  1946.0 1857.77  2117.3 1863.10  2404.3 1862.53  2802.5 1851.38
  2852.9 1852.77  2873.1 1849.87  2913.4 1852.53  2943.6 1849.51  3034.3 1848.12
  3790.1 1839.32  3971.5 1832.53  4898.6 1827.29  4974.7 1818.70  4975.2 1818.20
  4994.4 1818.70  4996.2 1822.94  4999.2 1823.62  5019.5 1824.03  5110.2 1822.14
  5463.0 1827.29  5854.2 1827.20  5956.0 1827.51  6271.2 1827.36  6491.2 1831.79
  6906.2 1855.41  6954.9 1855.32  7066.1 1848.88  7166.6 1858.46  8237.8 1859.44
#Mann=5,-1,0
  1833.6    0.05       0  4974.7   0.035       0  4994.4    0.05       0
  5854.2    0.12       0  5956.0    0.05       0
Bank Sta=4974.7,4994.4
Exp/Cntr=0.3,0.1

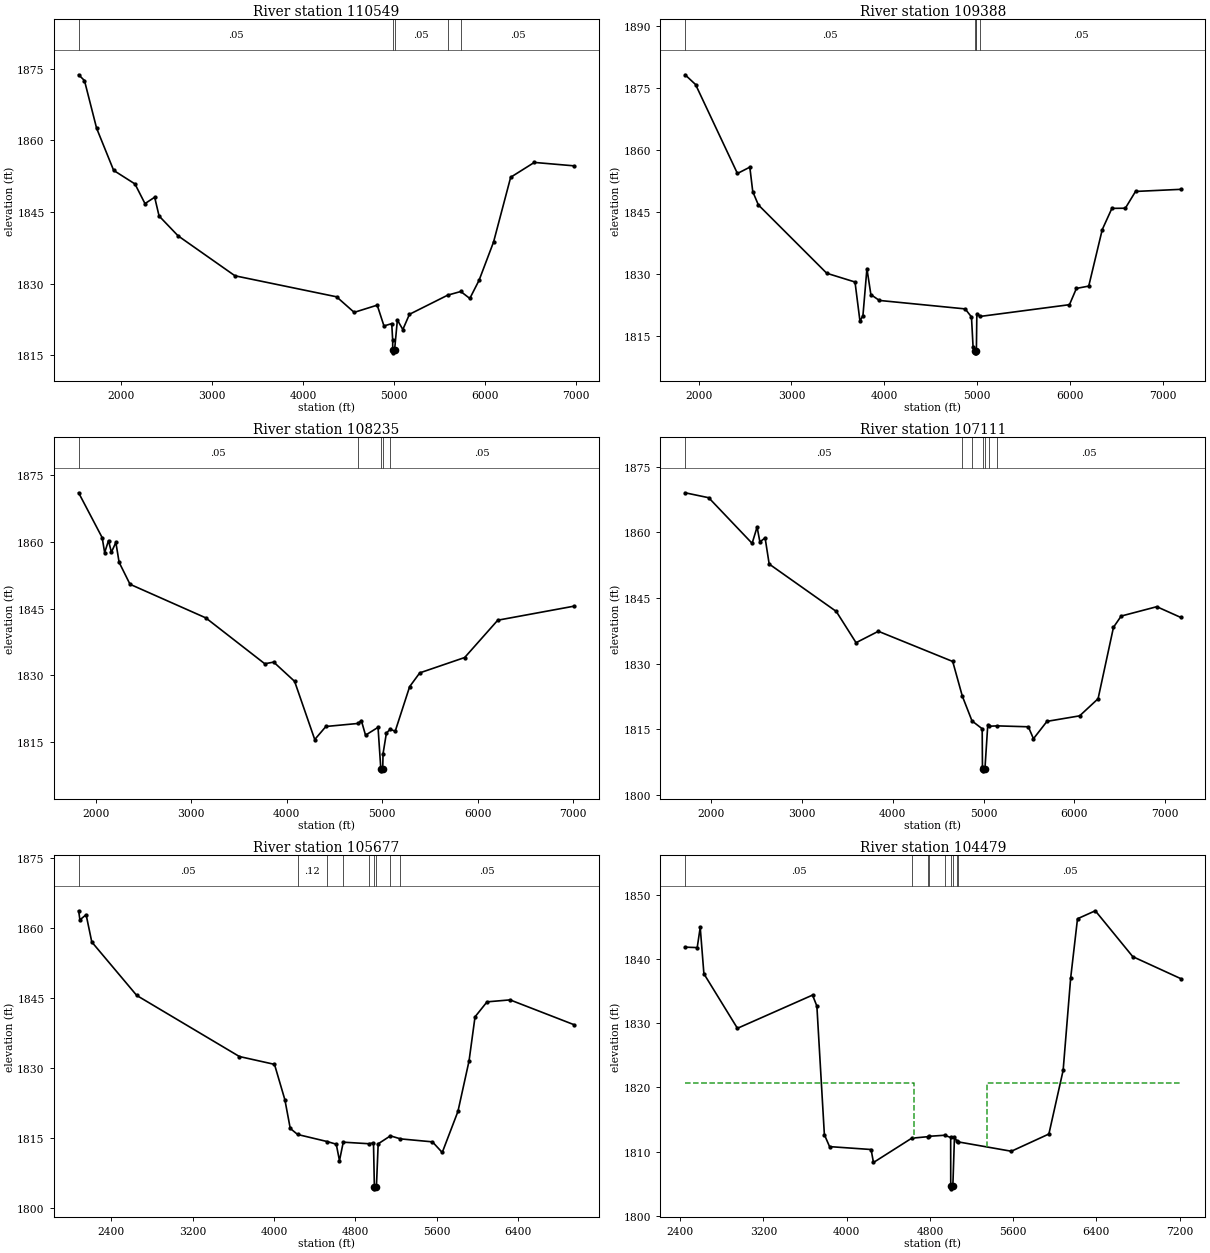
Type RM Length L Ch R = 1,110549,1161,1161,1161
BEGIN DESCRIPTION:
Cedar Creek 110549.03
END DESCRIPTION:
XS GIS Cut Line= 3
      1582249.27      6805704.68      1585504.44      6804524.14
      1587448.84      6804124.85
#Sta/Elev= 30
  1534.7 1873.74  1598.8 1872.53  1732.3 1862.54  1919.7 1853.71  2154.0 1850.87
  2264.1 1846.75  2370.5 1848.09  2419.0 1844.16  2628.0 1840.00  3253.4 1831.63
  4370.3 1827.23  4563.9 1823.97  4817.1 1825.48  4891.5 1821.12  4976.7 1821.61
  4987.3 1818.09  4987.5 1815.99  4988.0 1815.49  5007.5 1815.99  5038.7 1822.37
  5098.7 1820.37  5171.4 1823.56  5592.8 1827.58  5735.9 1828.34  5835.0 1826.88
  5937.1 1830.70  6096.0 1838.70  6284.2 1852.27  6544.1 1855.38  6982.3 1854.66
#Mann=5,-1,0
  1534.7    0.05       0  4987.5    0.05       0  5007.5    0.05       0
  5592.8    0.12       0  5735.9    0.05       0
Bank Sta=4987.5,5007.5
Exp/Cntr=0.3,0.1

Type RM Length L Ch R = 1,109388,1153,1153,1153
BEGIN DESCRIPTION:
Cedar Creek 109388.1
END DESCRIPTION:
XS GIS Cut Line= 3
      1582752.70      6806642.20      1585695.41      6805531.09
      1587744.01      6804749.84
#Sta/Elev= 30
  1854.5 1878.15  1967.3 1875.79  2418.3 1854.25  2551.7 1855.78  2583.4 1849.85
  2643.7 1846.64  3380.5 1830.09  3684.8 1827.97  3738.2 1818.49  3770.3 1819.85
  3813.1 1831.21  3855.8 1824.92  3946.9 1823.51  4871.3 1821.46  4939.4 1819.51
  4956.8 1812.15  4972.1 1811.32  4972.6 1810.82  4988.7 1810.82  4992.2 1811.32
  4997.3 1820.30  5034.9 1819.64  5994.9 1822.48  6069.8 1826.42  6202.5 1826.98
  6348.1 1840.66  6451.9 1845.80  6596.9 1845.84  6706.6 1849.90  7192.5 1850.41
#Mann=5,-1,0
  1854.5    0.05       0  4972.1    0.07       0  4988.7    0.12       0
  4992.2    0.05       0  5034.9    0.05       0
Bank Sta=4972.1,4992.2
Exp/Cntr=0.3,0.1

Type RM Length L Ch R = 1,108235,1124,1124,1124
BEGIN DESCRIPTION:
Mapping XS 726ba1b2
END DESCRIPTION:
XS GIS Cut Line= 4
      1583275.06      6807166.89      1584847.98      6806948.14
      1587087.56      6805963.77      1588056.29      6805333.57
#Sta/Elev= 30
  1820.6 1871.00  2067.3 1860.92  2093.1 1857.56  2133.5 1860.26  2163.8 1857.64
  2210.5 1859.86  2244.6 1855.38  2358.9 1850.45  3151.9 1842.91  3770.3 1832.60
  3863.7 1832.97  4082.6 1828.65  4293.5 1815.58  4410.2 1818.51  4745.7 1819.19
  4781.7 1819.85  4825.4 1816.56  4956.5 1818.32  4985.4 1809.05  4985.9 1808.55
  5005.6 1809.05  5008.8 1812.37  5043.9 1817.02  5082.0 1817.87  5136.5 1817.46
  5287.5 1827.46  5393.4 1830.55  5863.9 1834.00  6210.3 1842.38  7010.7 1845.54
#Mann=5,-1,0
  1820.6    0.05       0  4745.7    0.12       0  4985.4    0.07       0
  5005.6    0.12       0  5082.0    0.05       0
Bank Sta=4985.4,5005.6
Exp/Cntr=0.3,0.1

Type RM Length L Ch R = 1,107111,1434,1434,1434
BEGIN DESCRIPTION:
Cedar Creek 107110.57
END DESCRIPTION:
XS GIS Cut Line= 3
      1583246.64      6808454.69      1586215.38      6807061.47
      1588272.68      6806332.30
#Sta/Elev= 30
  1710.0 1869.06  1970.3 1867.93  2448.7 1857.50  2503.5 1861.23  2534.5 1857.83
  2591.9 1858.75  2636.8 1852.77  3376.2 1841.94  3594.3 1834.79  3840.1 1837.40
  4659.7 1830.50  4765.4 1822.60  4872.4 1816.91  4984.6 1815.12  4987.6 1806.28
  4994.8 1806.00  4995.3 1805.50  5015.1 1806.00  5046.0 1815.92  5056.2 1815.69
  5148.9 1815.78  5493.3 1815.57  5549.8 1812.84  5698.9 1816.81  6058.8 1818.07
  6262.1 1821.98  6431.9 1838.32  6516.8 1840.88  6909.3 1843.02  7172.1 1840.58
#Mann=7,-1,0
  1710.0    0.05       0  4765.4    0.12       0  4872.4    0.05       0
  4994.8   0.035       0  5015.1    0.05       0  5056.2    0.12       0
  5148.9    0.05       0
Bank Sta=4994.8,5015.1
Exp/Cntr=0.3,0.1

Type RM Length L Ch R = 1,105677,1198,1198,1198
BEGIN DESCRIPTION:
Mapping XS 5d2bff82
END DESCRIPTION:
XS GIS Cut Line= 4
      1584238.64      6808807.50      1585972.98      6808172.10
      1588045.89      6806984.60      1588451.05      6806496.33
#Sta/Elev= 30
  2079.8 1863.70  2092.4 1861.75  2153.4 1862.86  2209.1 1857.01  2651.0 1845.55
  3660.0 1832.46  4004.8 1830.78  4107.0 1823.19  4159.7 1817.05  4232.3 1815.75
  4521.7 1814.24  4612.0 1813.67  4643.6 1810.14  4680.7 1814.10  4932.1 1813.77
  4977.9 1813.94  4986.5 1804.60  4987.0 1804.10  5006.8 1804.60  5024.0 1813.75
  5144.4 1815.46  5242.9 1814.81  5557.3 1814.17  5653.6 1811.89  5807.7 1820.68
  5916.9 1831.50  5975.9 1840.97  6093.9 1844.18  6320.1 1844.60  6950.3 1839.27
#Mann=9,-1,0
  2079.8    0.05       0  4232.3    0.12       0  4521.7    0.05       0
  4680.7    0.12       0  4932.1    0.05       0  4986.5   0.035       0
  5006.8    0.05       0  5144.4    0.12       0  5242.9    0.05       0
Bank Sta=4986.5,5006.8
Exp/Cntr=0.3,0.1

Type RM Length L Ch R = 1,104479,2006,2006,2006
BEGIN DESCRIPTION:
Cedar Creek 104479.11
END DESCRIPTION:
XS GIS Cut Line= 3
      1585321.70      6809978.58      1587372.50      6808448.62
      1588598.60      6806614.89
#Sta/Elev= 30
  2446.3 1841.84  2562.7 1841.77  2591.7 1844.91  2627.1 1837.70  2949.5 1829.21
  3671.6 1834.38  3713.3 1832.67  3785.4 1812.66  3835.3 1810.80  4234.5 1810.35
  4257.5 1808.33  4625.3 1812.11  4783.3 1812.35  4788.6 1812.40  4941.4 1812.57
  4999.7 1812.22  5000.3 1804.73  5000.8 1804.23  5020.8 1804.73  5036.1 1812.27
  5057.8 1811.70  5074.1 1811.53  5583.1 1810.08  5944.0 1812.76  6081.1 1822.67
  6153.2 1837.00  6219.2 1846.26  6390.4 1847.50  6750.8 1840.36  7210.8 1836.95
#Mann=9,-1,0
  2446.3    0.05       0  4625.3    0.12       0  4783.3    0.05       0
  4788.6    0.12       0  4941.4    0.05       0  5000.3   0.035       0
  5020.8    0.05       0  5057.8    0.12       0  5074.1    0.05       0
#XS Ineff=2,0
    0.00 4647.80 1820.68 5352.20    0.00 1820.68
Permanent Ineff=
       F       F
Bank Sta=5000.3,5020.8
Exp/Cntr=0.3,0.1

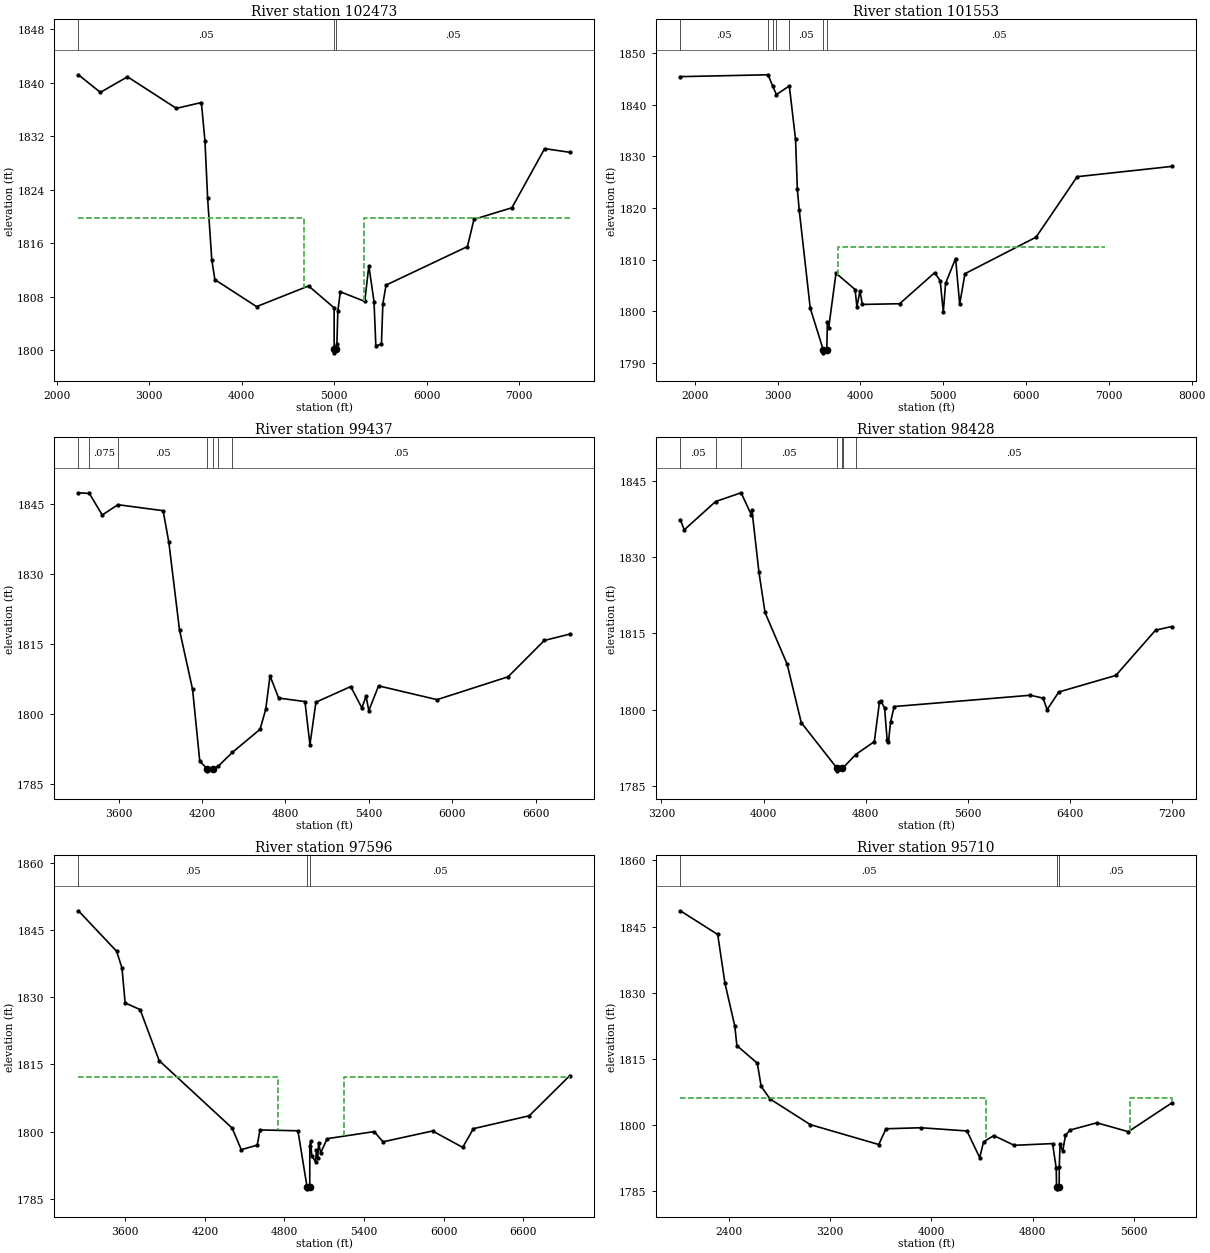
Type RM Length L Ch R = 1,102473,920,920,920
BEGIN DESCRIPTION:
Mapping XS d522e485
END DESCRIPTION:
XS GIS Cut Line= 5
      1585400.04      6810385.66      1586488.60      6809557.52
      1587545.89      6809041.89      1588499.02      6808979.39
      1589780.11      6807698.30
#Sta/Elev= 30
  2235.8 1841.17  2473.0 1838.54  2766.1 1840.87  3294.2 1836.15  3564.6 1837.02
  3603.6 1831.23  3632.0 1822.78  3677.1 1813.50  3710.8 1810.54  4161.4 1806.51
  4723.3 1809.60  4999.5 1806.33  4999.6 1800.10  5000.0 1799.60  5016.0 1800.10
  5029.5 1800.99  5039.6 1805.83  5066.6 1808.73  5330.2 1807.29  5374.8 1812.62
  5430.4 1807.27  5450.4 1800.65  5510.6 1800.89  5526.3 1806.97  5560.7 1809.73
  6440.3 1815.49  6511.0 1819.56  6921.1 1821.29  7274.7 1830.13  7546.8 1829.58
#Mann=3,-1,0
  2235.8    0.05       0  4999.6   0.035       0  5016.0    0.05       0
#XS Ineff=2,0
    0.00 4678.30 1819.77 5321.70    0.00 1819.77
Permanent Ineff=
       F       F
Bank Sta=4999.6,5016
Exp/Cntr=0.3,0.1

Type RM Length L Ch R = 1,101553,2116,2116,2116
BEGIN DESCRIPTION:
Cedar Creek 101553.36
END DESCRIPTION:
XS GIS Cut Line= 3
      1585419.40      6810944.27      1588240.55      6809446.89
      1590323.89      6807667.36
#Sta/Elev= 30
  1825.4 1845.43  2884.6 1845.79  2942.6 1843.54  2985.8 1841.95  3141.4 1843.64
  3216.6 1833.31  3238.6 1823.64  3260.5 1819.67  3394.1 1800.62  3552.9 1792.46
  3553.9 1791.96  3593.9 1792.46  3601.0 1797.84  3617.3 1796.86  3705.3 1807.38
  3935.8 1804.22  3957.8 1800.83  3994.1 1803.93  4023.7 1801.33  4474.1 1801.47
  4896.9 1807.48  4962.8 1805.93  5001.2 1799.87  5028.5 1805.42  5149.3 1810.22
  5198.7 1801.37  5262.4 1807.28  6120.9 1814.35  6617.1 1826.06  7759.2 1828.05
#Mann=7,-1,0
  1825.4    0.05       0  2884.6   0.075       0  2942.6    0.05       0
  2985.8   0.075       0  3141.4    0.05       0  3552.9   0.035       0
  3593.9    0.05       0
#XS Ineff=1,-1
 3732.00 6959.40 1812.52
Permanent Ineff=
       F
Bank Sta=3552.9,3593.9
Exp/Cntr=0.3,0.1

Type RM Length L Ch R = 1,99437,1009,1009,1009
BEGIN DESCRIPTION:
Cedar Creek 99436.7
END DESCRIPTION:
XS GIS Cut Line= 3
      1586369.04      6810772.40      1588014.86      6810355.74
      1589848.16      6810251.58
#Sta/Elev= 30
  3311.3 1847.44  3390.0 1847.30  3482.5 1842.66  3595.7 1844.88  3920.5 1843.59
  3961.5 1836.81  4038.3 1817.97  4132.4 1805.19  4183.9 1789.80  4235.4 1788.22
  4236.4 1787.72  4277.0 1788.22  4315.5 1788.68  4418.4 1791.68  4617.5 1796.63
  4658.5 1800.95  4689.2 1808.12  4751.3 1803.35  4940.4 1802.60  4976.3 1793.33
  5019.2 1802.46  5269.6 1805.82  5349.7 1801.24  5379.8 1803.75  5399.8 1800.64
  5469.9 1805.97  5890.6 1803.01  6401.4 1807.92  6661.8 1815.72  6845.3 1817.09
#Mann=7,-1,0
  3311.3    0.05       0  3390.0   0.075       0  3595.7    0.05       0
  4235.4   0.035       0  4277.0    0.05       0  4315.5     0.1       0
  4418.4    0.05       0
Bank Sta=4235.4,4277
Exp/Cntr=0.3,0.1

Type RM Length L Ch R = 1,98428,832,832,832
BEGIN DESCRIPTION:
Cedar Creek 98428.23
END DESCRIPTION:
XS GIS Cut Line= 3
      1586061.72      6811116.16      1587702.36      6810959.91
      1589827.36      6810381.78
#Sta/Elev= 30
  3348.3 1837.34  3379.2 1835.35  3624.8 1840.92  3824.2 1842.64  3904.0 1838.35
  3909.0 1839.33  3964.4 1827.00  4012.0 1819.09  4185.3 1808.92  4295.8 1797.43
  4576.4 1788.44  4577.4 1787.94  4618.0 1788.44  4621.8 1788.48  4721.5 1791.13
  4868.4 1793.69  4908.6 1801.47  4918.7 1801.72  4948.8 1800.28  4968.9 1794.00
  4978.9 1793.52  4995.2 1797.51  5023.8 1800.59  6090.9 1802.81  6190.9 1802.24
  6222.0 1799.97  6314.0 1803.45  6760.9 1806.71  7071.8 1815.61  7198.6 1816.33
#Mann=7,-1,0
  3348.3    0.05       0  3624.8   0.075       0  3824.2    0.05       0
  4576.4   0.035       0  4618.0    0.05       0  4621.8     0.1       0
  4721.5    0.05       0
Bank Sta=4576.4,4618
Exp/Cntr=0.3,0.1

Type RM Length L Ch R = 1,97596,1886,1886,1886
BEGIN DESCRIPTION:
Cedar Creek 97595.94
END DESCRIPTION:
XS GIS Cut Line= 3
      1586332.60      6812220.31      1587994.02      6811683.87
      1589701.17      6810726.20
#Sta/Elev= 30
  3247.2 1849.26  3535.0 1840.24  3575.5 1836.50  3599.1 1828.73  3712.1 1827.23
  3855.4 1815.87  4405.2 1800.84  4474.6 1796.01  4594.8 1797.02  4615.8 1800.41
  4901.5 1800.22  4969.8 1787.78  4970.3 1787.28  4990.6 1787.78  4991.0 1796.85
  4997.4 1797.88  5005.7 1794.68  5035.0 1793.29  5040.8 1795.88  5051.0 1794.17
  5056.7 1797.60  5072.7 1795.28  5121.8 1798.46  5475.8 1800.04  5542.8 1797.76
  5915.9 1800.18  6143.0 1796.52  6224.0 1800.69  6645.0 1803.57  6950.5 1812.52
#Mann=3,-1,0
  3247.2    0.05       0  4969.8   0.035       0  4990.6    0.05       0
#XS Ineff=2,0
    0.00 4747.70 1812.24 5252.30    0.00 1812.24
Permanent Ineff=
       F       F
Bank Sta=4969.8,4990.6
Exp/Cntr=0.3,0.1

Type RM Length L Ch R = 1,95710,1829,1829,1829
BEGIN DESCRIPTION:
Cedar Creek 95710.1
END DESCRIPTION:
XS GIS Cut Line= 3
      1586452.51      6812470.26      1589412.60      6812070.96
      1590089.70      6811489.35
#Sta/Elev= 30
  2018.4 1848.59  2313.5 1843.22  2370.5 1832.22  2448.3 1822.48  2464.9 1818.04
  2626.3 1814.06  2656.6 1808.81  2727.3 1805.94  3045.1 1800.14  3585.0 1795.64
  3642.0 1799.21  3917.9 1799.44  4281.2 1798.71  4382.1 1792.67  4412.4 1796.25
  4493.1 1797.66  4654.6 1795.46  4957.3 1795.85  4986.3 1790.23  4988.4 1786.10
  4988.9 1785.60  5009.3 1786.10  5010.2 1790.48  5016.3 1795.78  5037.1 1794.12
  5059.1 1797.70  5094.2 1798.91  5307.1 1800.56  5555.1 1798.55  5897.9 1805.05
#Mann=3,-1,0
  2018.4    0.05       0  4988.4   0.035       0  5009.3    0.05       0
#XS Ineff=2,0
    0.00 4433.10 1806.25 5566.90    0.00 1806.25
Permanent Ineff=
       F       F
Bank Sta=4988.4,5009.3
Exp/Cntr=0.3,0.1

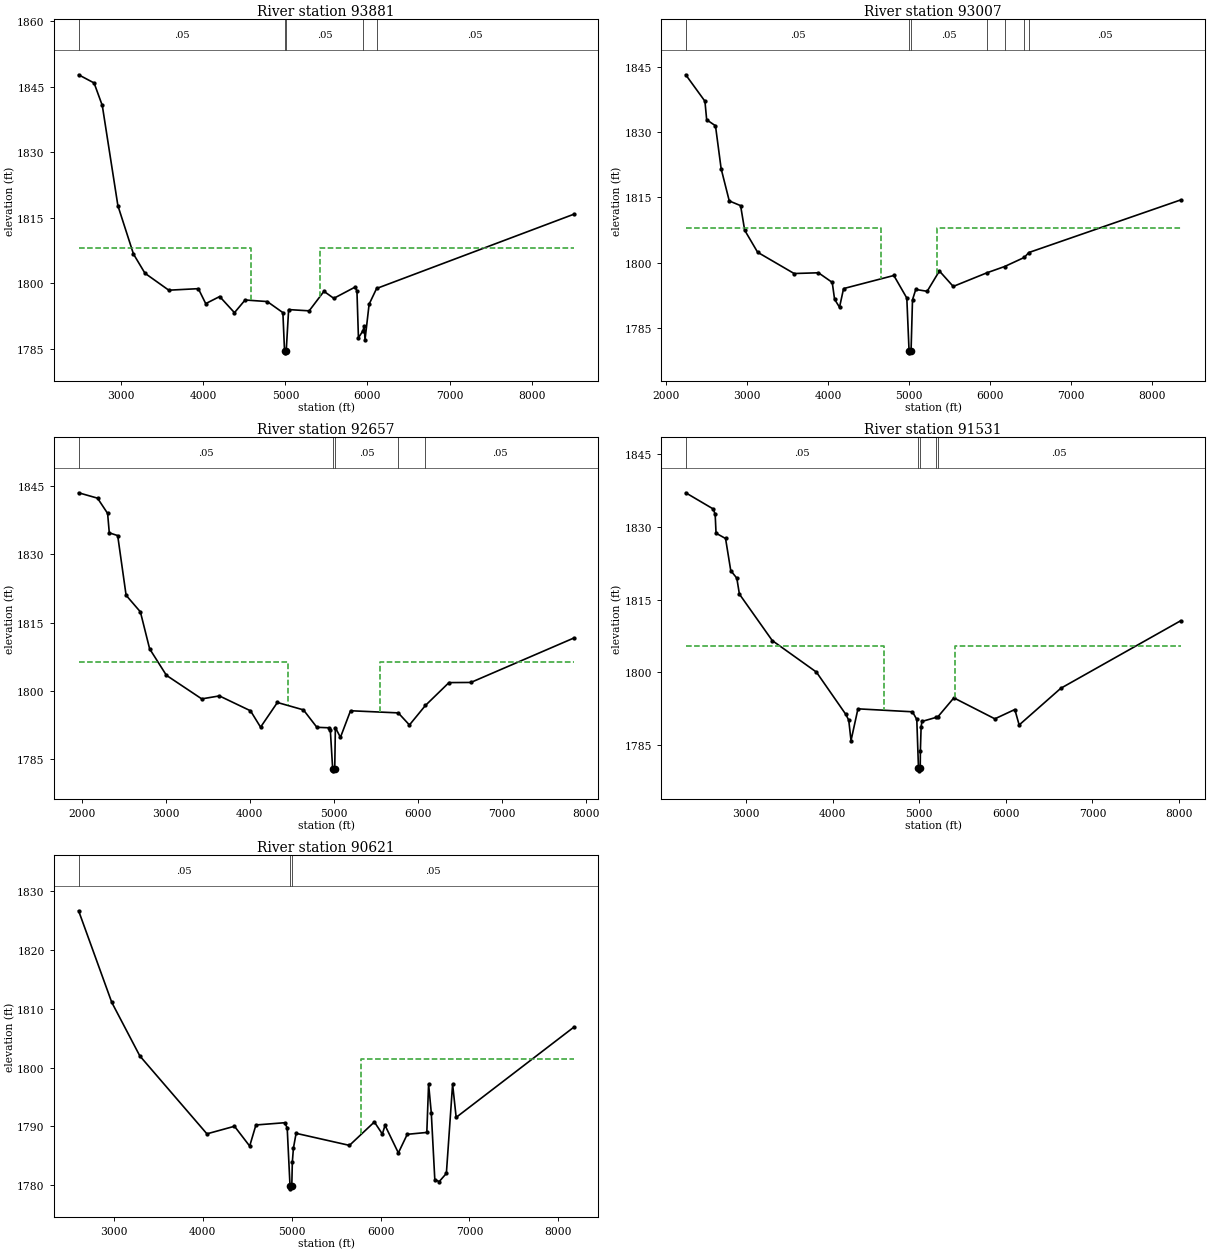
Type RM Length L Ch R = 1,93881,874,874,874
BEGIN DESCRIPTION:
Cedar Creek 93945.7
END DESCRIPTION:
XS GIS Cut Line= 4
      1586426.46      6812591.79      1588956.05      6812645.62
      1590233.83      6812597.01      1592428.27      6812249.79
#Sta/Elev= 30
  2480.3 1847.70  2668.9 1845.83  2768.9 1840.68  2958.9 1817.79  3149.0 1806.72
  3289.0 1802.33  3579.1 1798.46  3939.2 1798.81  4029.2 1795.39  4199.2 1797.01
  4379.3 1793.32  4509.3 1796.22  4779.4 1795.86  4969.4 1793.33  4989.3 1784.64
  4989.8 1784.14  5010.2 1784.64  5039.4 1794.03  5289.6 1793.74  5469.7 1798.20
  5589.8 1796.60  5850.0 1799.18  5871.8 1798.26  5890.0 1787.56  5945.0 1789.19
  5960.1 1790.22  5970.1 1787.13  6020.1 1795.26  6111.2 1798.85  8510.9 1815.80
#Mann=5,-1,0
  2480.3    0.05       0  4989.3   0.035       0  5010.2    0.05       0
  5945.0    0.12       0  6111.2    0.05       0
#XS Ineff=2,0
    0.00 4580.60 1808.07 5419.40    0.00 1808.07
Permanent Ineff=
       F       F
Bank Sta=4989.3,5010.2
Exp/Cntr=0.3,0.1

Type RM Length L Ch R = 1,93007,350,350,350
BEGIN DESCRIPTION:
Cedar Creek 93007.59
END DESCRIPTION:
XS GIS Cut Line= 3
      1586548.00      6813199.43      1589299.75      6813129.98
      1592636.62      6812789.72
#Sta/Elev= 30
  2242.4 1843.11  2479.5 1837.05  2500.8 1832.80  2609.5 1831.43  2679.5 1821.58
  2779.6 1814.21  2919.6 1813.13  2969.6 1807.51  3129.7 1802.45  3579.8 1797.58
  3879.9 1797.75  4050.0 1795.55  4078.9 1791.69  4140.0 1789.85  4190.0 1794.13
  4810.2 1797.13  4970.3 1791.96  4997.8 1779.91  4998.3 1779.41  5022.7 1779.91
  5040.5 1791.57  5080.7 1793.93  5221.4 1793.51  5372.2 1798.16  5543.1 1794.62
  5960.6 1797.76  6176.8 1799.18  6421.6 1801.28  6474.7 1802.38  8349.2 1814.44
#Mann=7,-1,0
  2242.4    0.05       0  4997.8    0.05       0  5022.7    0.05       0
  5960.6    0.12       0  6176.8    0.05       0  6421.6    0.12       0
  6474.7    0.05       0
#XS Ineff=2,0
    0.00 4653.50 1808.00 5346.50    0.00 1808.00
Permanent Ineff=
       F       F
Bank Sta=4997.8,5022.7
Exp/Cntr=0.3,0.1

Type RM Length L Ch R = 1,92657,1126,1126,1126
BEGIN DESCRIPTION:
Cedar Creek 92656.94
END DESCRIPTION:
XS GIS Cut Line= 3
      1586469.89      6813347.00      1589516.76      6813347.00
      1592355.29      6813208.11
#Sta/Elev= 30
  1965.1 1843.43  2190.2 1842.25  2310.2 1838.91  2330.2 1834.65  2430.2 1834.05
  2530.2 1820.97  2700.2 1817.33  2810.2 1809.23  3010.2 1803.42  3430.2 1798.26
  3640.2 1798.91  4010.2 1795.65  4130.2 1792.06  4330.2 1797.47  4640.2 1795.85
  4800.2 1792.03  4950.2 1791.92  4960.2 1791.39  4987.7 1782.99  4988.2 1782.49
  5012.6 1782.99  5020.2 1791.97  5080.3 1789.82  5200.4 1795.66  5768.4 1795.19
  5901.3 1792.54  6091.6 1796.82  6371.8 1801.83  6632.1 1801.86  7853.9 1811.57
#Mann=5,-1,0
  1965.1    0.05       0  4987.7    0.05       0  5012.6    0.05       0
  5768.4    0.12       0  6091.6    0.05       0
#XS Ineff=2,0
    0.00 4452.60 1806.37 5547.40    0.00 1806.37
Permanent Ineff=
       F       F
Bank Sta=4987.7,5012.6
Exp/Cntr=0.3,0.1

Type RM Length L Ch R = 1,91531,910,910,910
BEGIN DESCRIPTION:
Cedar Creek 91531.26
END DESCRIPTION:
XS GIS Cut Line= 3
      1586504.64      6814267.14      1589212.94      6814232.41
      1592216.45      6814006.72
#Sta/Elev= 30
  2299.9 1837.03  2618.9 1833.68  2640.3 1832.55  2650.3 1828.69  2760.3 1827.60
  2820.3 1820.98  2890.3 1819.42  2920.3 1816.13  3300.3 1806.54  3810.4 1800.04
  4150.4 1791.31  4184.0 1790.12  4210.4 1785.91  4290.4 1792.46  4920.5 1791.85
  4970.5 1790.27  4990.2 1780.17  4990.6 1779.67  5010.2 1780.17  5012.0 1783.70
  5020.5 1788.77  5030.5 1789.86  5194.4 1790.70  5213.0 1790.79  5398.8 1794.72
  5872.9 1790.40  6103.6 1792.32  6153.7 1789.13  6635.1 1796.70  8020.4 1810.63
#Mann=5,-1,0
  2299.9    0.05       0  4990.2    0.05       0  5010.2    0.05       0
  5194.4    0.12       0  5213.0    0.05       0
#XS Ineff=2,0
    0.00 4588.10 1805.36 5411.90    0.00 1805.36
Permanent Ineff=
       F       F
Bank Sta=4990.2,5010.2
Exp/Cntr=0.3,0.1

Type RM Length L Ch R = 1,90621,561,561,561
BEGIN DESCRIPTION:
Cedar Creek 90621.36
END DESCRIPTION:
XS GIS Cut Line= 3
      1586669.50      6814787.97      1589065.37      6815013.66
      1592225.10      6814978.94
#Sta/Elev= 30
  2604.6 1826.67  2977.4 1811.10  3293.1 1801.99  4047.9 1788.74  4357.8 1790.03
  4528.6 1786.66  4598.9 1790.25  4920.3 1790.63  4950.4 1789.80  4982.3 1779.89
  4982.7 1779.39  5002.2 1779.89  5008.4 1783.95  5020.7 1786.32  5050.7 1788.83
  5650.7 1786.78  5930.8 1790.76  6020.8 1788.71  6050.8 1790.19  6200.8 1785.50
  6300.8 1788.66  6520.8 1788.98  6540.8 1797.20  6570.8 1792.37  6610.8 1780.94
  6660.8 1780.63  6740.8 1782.02  6810.8 1797.19  6850.8 1791.54  8171.0 1806.84
#Mann=3,-1,0
  2604.6    0.05       0  4982.3    0.05       0  5002.2    0.05       0
#XS Ineff=2,0
       0                 5781.30    0.00 1801.44
Permanent Ineff=
       F       F
Bank Sta=4982.3,5002.2
Exp/Cntr=0.3,0.1