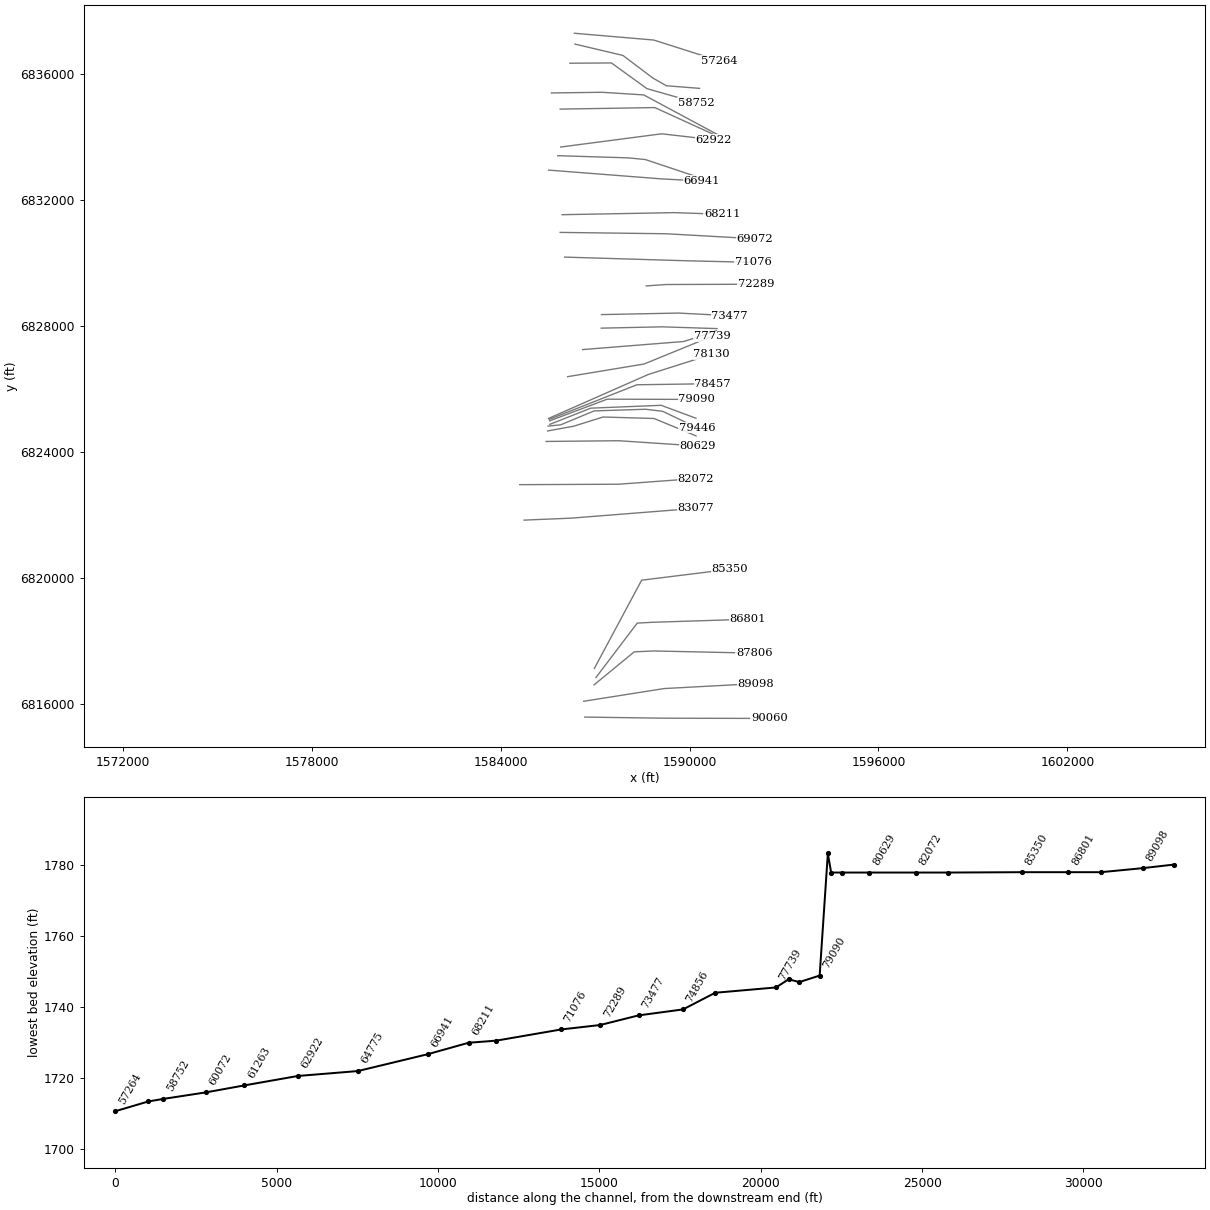
HEC-RAS study Cedar Creek.prj: Cedar Creek Base Level Engineering

--- Cedar Creek.g01 (geometry) --- (continued)

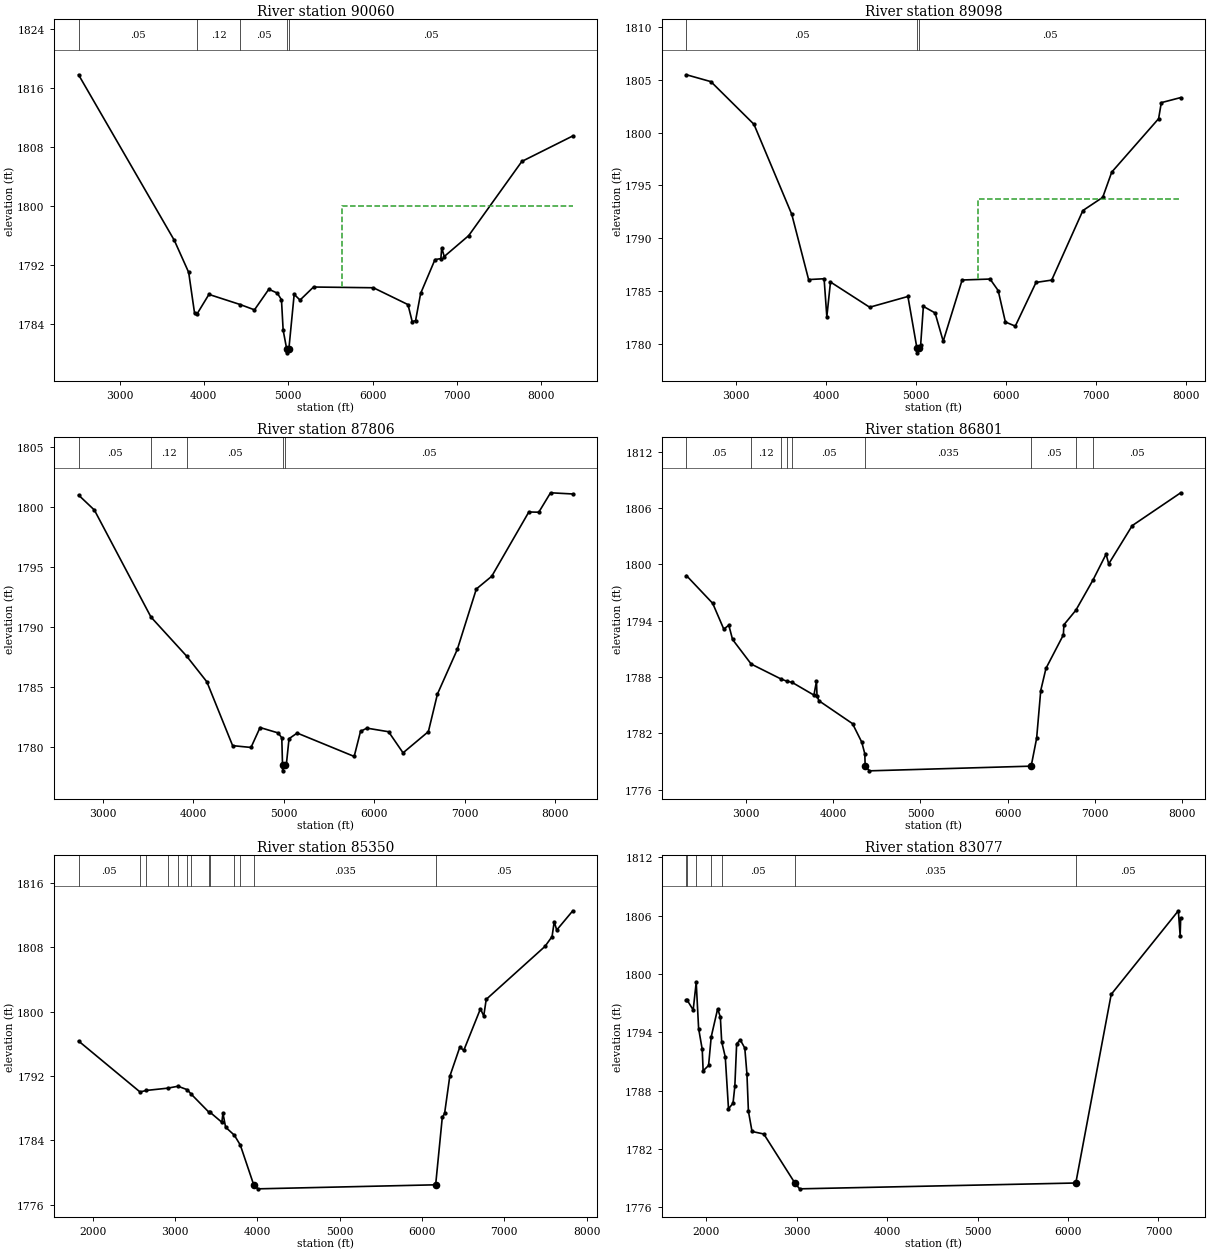
Type RM Length L Ch R = 1,90060,962,962,962
BEGIN DESCRIPTION:
Cedar Creek 90060.38
END DESCRIPTION:
XS GIS Cut Line= 3
      1586669.51      6815577.90      1589152.18      6815543.18
      1592528.96      6815534.50
#Sta/Elev= 30
  2514.4 1817.78  3650.0 1795.36  3820.0 1791.03  3890.0 1785.48  3917.8 1785.38
  4060.0 1788.05  4432.9 1786.67  4600.1 1785.96  4770.1 1788.75  4870.1 1788.23
  4920.1 1787.33  4940.1 1783.20  4982.5 1780.64  4983.0 1780.14  5007.7 1780.64
  5070.8 1788.06  5140.1 1787.28  5300.1 1789.05  6010.1 1788.95  6420.1 1786.67
  6470.1 1784.37  6510.1 1784.50  6570.1 1788.18  6740.1 1792.76  6810.1 1792.90
  6820.1 1794.36  6850.1 1793.18  7140.1 1796.01  7770.1 1806.05  8374.1 1809.50
#Mann=5,-1,0
  2514.4    0.05       0  3917.8    0.12       0  4432.9    0.05       0
  4982.5    0.05       0  5007.7    0.05       0
#XS Ineff=2,0
       0                 5636.20    0.00 1800.08
Permanent Ineff=
       F       F
Bank Sta=4982.5,5007.7
Exp/Cntr=0.3,0.1

Type RM Length L Ch R = 1,89098,1292,1292,1292
BEGIN DESCRIPTION:
Cedar Creek 89097.76
END DESCRIPTION:
XS GIS Cut Line= 3
      1586634.64      6816080.20      1589186.73      6816483.85
      1592090.22      6816640.09
#Sta/Elev= 30
  2448.0 1805.48  2719.3 1804.83  3197.6 1800.79  3617.9 1792.26  3805.0 1786.08
  3977.1 1786.16  4007.5 1782.56  4048.0 1785.85  4483.3 1783.46  4908.6 1784.48
  5007.4 1779.64  5007.9 1779.14  5032.7 1779.64  5050.1 1779.90  5080.2 1783.54
  5210.3 1782.92  5300.5 1780.24  5510.8 1786.04  5821.2 1786.13  5911.4 1785.04
  5991.5 1782.06  6101.6 1781.67  6332.0 1785.81  6506.0 1786.03  6852.7 1792.62
  7073.0 1793.87  7173.2 1796.26  7693.9 1801.32  7724.0 1802.84  7939.5 1803.32
#Mann=3,-1,0
  2448.0    0.05       0  5007.4    0.05       0  5032.7    0.05       0
#XS Ineff=2,0
       0                 5686.10    0.00 1793.68
Permanent Ineff=
       F       F
Bank Sta=5007.4,5032.7
Exp/Cntr=0.3,0.1

Type RM Length L Ch R = 1,87806,1005,1005,1005
BEGIN DESCRIPTION:
Cedar Creek 87806.22
END DESCRIPTION:
XS GIS Cut Line= 4
      1586964.72      6816602.23      1588240.81      6817650.64
      1588874.40      6817678.60      1592050.70      6817609.17
#Sta/Elev= 30
  2732.2 1800.99  2907.0 1799.74  3532.5 1790.82  3926.1 1787.57  4150.4 1785.42
  4435.1 1780.10  4638.2 1779.95  4738.3 1781.61  4938.5 1781.16  4978.5 1780.75
  4986.6 1778.50  4987.1 1778.00  5011.9 1778.50  5028.5 1778.50  5058.6 1780.68
  5148.6 1781.15  5778.7 1779.20  5848.7 1781.29  5918.8 1781.56  6158.8 1781.26
  6318.9 1779.50  6598.9 1781.27  6698.9 1784.40  6919.0 1788.13  7129.0 1793.16
  7299.1 1794.22  7709.2 1799.58  7819.2 1799.56  7949.2 1801.18  8195.0 1801.08
#Mann=5,-1,0
  2732.2    0.05       0  3532.5    0.12       0  3926.1    0.05       0
  4986.6    0.05       0  5011.9    0.05       0
Bank Sta=4986.6,5011.9
Exp/Cntr=0.3,0.1

Type RM Length L Ch R = 1,86801,1451,1451,1451
BEGIN DESCRIPTION:
Cedar Creek 86800.59
END DESCRIPTION:
XS GIS Cut Line= 4
      1587025.47      6816836.61      1588336.21      6818564.01
      1588831.00      6818590.05      1591841.62      6818685.49
#Sta/Elev= 30
  2313.0 1798.80  2614.0 1795.85  2741.5 1793.10  2799.1 1793.52  2842.0 1792.00
  3055.9 1789.38  3398.1 1787.79  3462.9 1787.56  3525.1 1787.43  3776.7 1786.07
  3805.8 1787.54  3812.1 1786.00  3833.6 1785.47  4219.7 1783.03  4325.9 1781.06
  4361.2 1779.81  4365.0 1778.50  4414.7 1778.00  6271.5 1778.50  6334.4 1781.47
  6381.6 1786.56  6441.6 1788.92  6641.7 1792.49  6647.3 1793.56  6784.5 1795.11
  6980.3 1798.31  7132.0 1801.09  7162.0 1800.05  7432.1 1804.13  7989.0 1807.63
#Mann=9,-1,0
  2313.0    0.05       0  3055.9    0.12       0  3398.1    0.05       0
  3462.9    0.12       0  3525.1    0.05       0  4365.0   0.035       0
  6271.5    0.05       0  6784.5    0.12       0  6980.3    0.05       0
Bank Sta=4365,6271.5
Exp/Cntr=0.3,0.1

Type RM Length L Ch R = 1,85350,2273,2273,2273
BEGIN DESCRIPTION:
Cedar Creek 85349.3
END DESCRIPTION:
XS GIS Cut Line= 3
      1586973.35      6817123.02      1588475.10      6819926.86
      1591278.90      6820274.08
#Sta/Elev= 30
  1825.9 1796.34  2572.7 1790.02  2649.8 1790.21  2909.3 1790.49  3034.1 1790.73
  3146.8 1790.30  3193.8 1789.76  3406.0 1787.55  3420.2 1787.53  3567.2 1786.26
  3580.5 1787.39  3612.6 1785.65  3718.7 1784.66  3791.6 1783.43  3954.4 1778.50
  4004.9 1778.00  6165.3 1778.50  6245.9 1786.86  6274.1 1787.36  6336.6 1791.94
  6457.5 1795.54  6507.9 1795.20  6709.4 1800.33  6749.7 1799.45  6779.9 1801.51
  7493.9 1808.08  7580.0 1809.30  7606.2 1811.15  7636.4 1810.11  7831.8 1812.50
#Mann=13,-1,0
  1825.9    0.05       0  2572.7    0.12       0  2649.8    0.05       0
  2909.3    0.12       0  3034.1    0.05       0  3146.8    0.12       0
  3193.8    0.05       0  3406.0    0.12       0  3420.2    0.05       0
  3718.7    0.12       0  3791.6    0.05       0  3954.4   0.035       0
  6165.3    0.05       0
Bank Sta=3954.4,6165.3
Exp/Cntr=0.3,0.1

Type RM Length L Ch R = 1,83077,1005,1005,1005
BEGIN DESCRIPTION:
Mapping XS a5bbfd69
END DESCRIPTION:
XS GIS Cut Line= 3
      1584740.93      6821835.09      1586233.94      6821897.59
      1590191.11      6822210.00
#Sta/Elev= 30
  1782.2 1797.31  1790.8 1797.29  1856.3 1796.30  1889.7 1799.14  1916.4 1794.39
  1956.4 1792.24  1966.3 1790.04  2026.5 1790.59  2055.6 1793.53  2126.6 1796.41
  2156.6 1795.58  2171.4 1793.03  2211.0 1791.47  2246.7 1786.13  2296.7 1786.71
  2316.7 1788.44  2336.8 1792.83  2376.8 1793.22  2426.8 1792.38  2450.6 1789.71
  2466.9 1785.88  2506.9 1783.80  2637.0 1783.54  2980.5 1778.50  3033.0 1777.90
  6086.3 1778.50  6477.5 1797.90  7219.8 1806.50  7239.9 1803.95  7246.0 1805.77
#Mann=7,-1,0
  1782.2     0.1       0  1790.8   0.075       0  1889.7    0.05       0
  2055.6   0.075       0  2171.4    0.05       0  2980.5   0.035       0
  6086.3    0.05       0
Bank Sta=2980.5,6086.3
Exp/Cntr=0.3,0.1

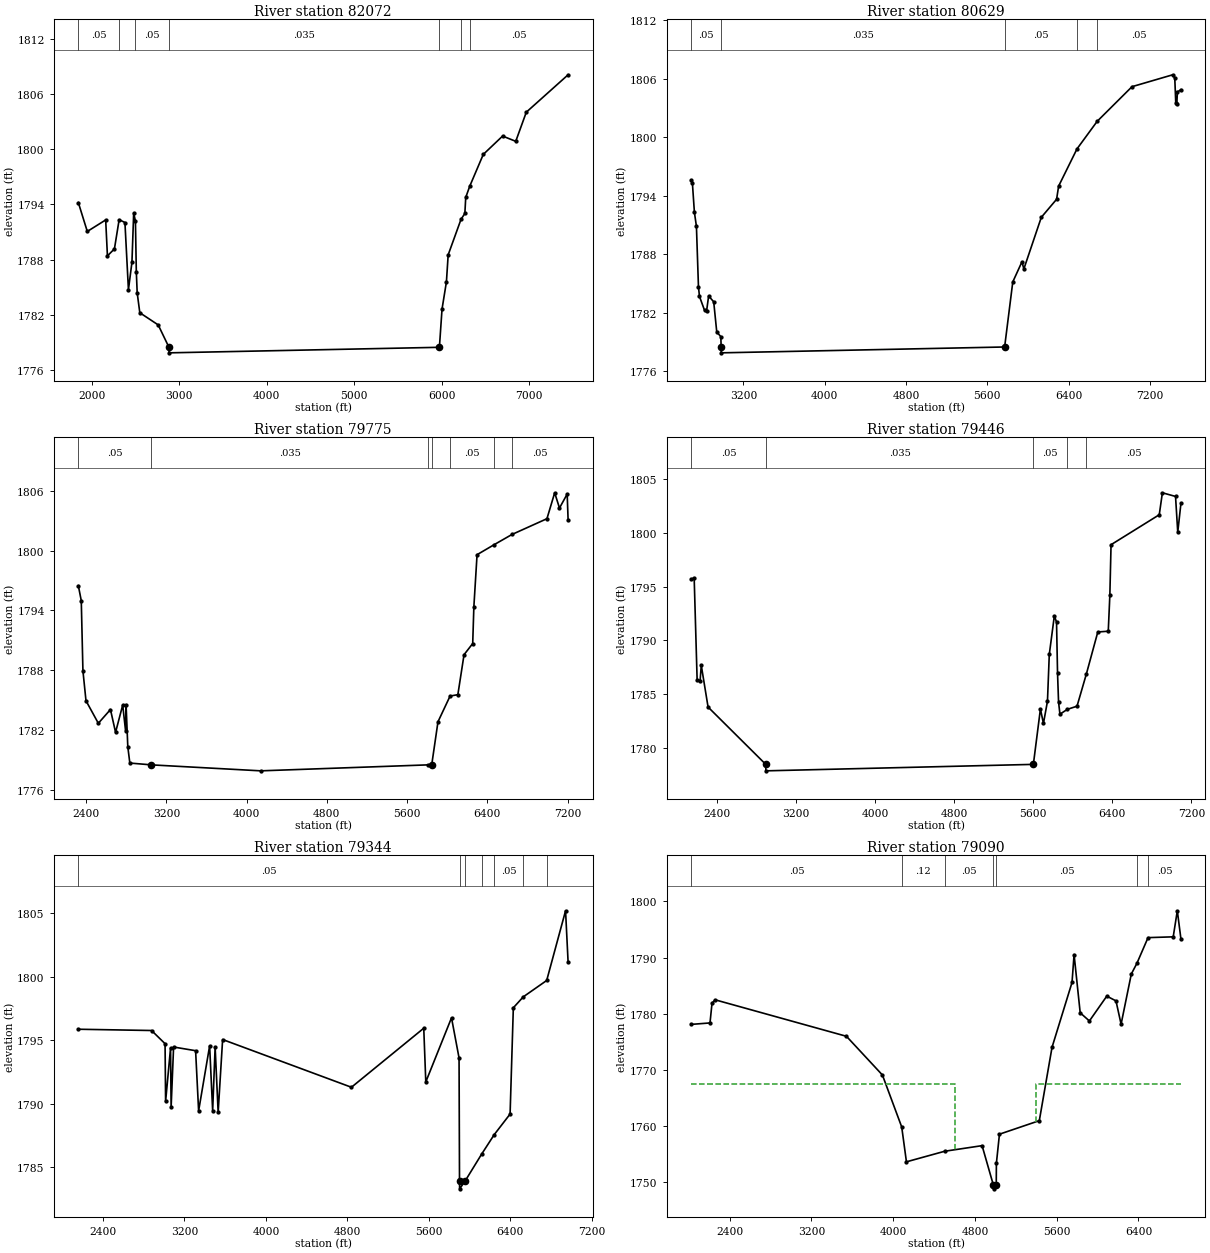
Type RM Length L Ch R = 1,82072,1443,1443,1443
BEGIN DESCRIPTION:
Cedar Creek 82071.66
END DESCRIPTION:
XS GIS Cut Line= 3
      1584602.72      6822961.58      1587741.59      6822975.47
      1590191.46      6823155.91
#Sta/Elev= 30
  1847.8 1794.20  1950.1 1791.07  2160.1 1792.32  2180.1 1788.42  2260.1 1789.18
  2313.9 1792.35  2380.1 1792.04  2420.1 1784.75  2460.1 1787.72  2480.1 1793.07
  2500.1 1792.19  2510.1 1786.72  2520.1 1784.41  2550.1 1782.25  2760.1 1780.93
  2883.2 1778.50  2884.3 1777.90  5972.8 1778.50  6002.9 1782.65  6053.0 1785.60
  6073.0 1788.53  6219.9 1792.39  6263.6 1793.02  6273.6 1794.76  6319.0 1795.97
  6474.1 1799.43  6694.7 1801.42  6845.1 1800.85  6965.5 1804.01  7443.2 1808.07
#Mann=7,-1,0
  1847.8    0.05       0  2313.9   0.075       0  2500.1    0.05       0
  2883.2   0.035       0  5972.8    0.05       0  6219.9   0.075       0
  6319.0    0.05       0
Bank Sta=2883.2,5972.8
Exp/Cntr=0.3,0.1

Type RM Length L Ch R = 1,80629,854,854,854
BEGIN DESCRIPTION:
Cedar Creek 80628.89
END DESCRIPTION:
XS GIS Cut Line= 3
      1585443.19      6824334.63      1587748.53      6824357.41
      1590255.45      6824190.75
#Sta/Elev= 30
  2686.7 1795.59  2698.5 1795.35  2718.5 1792.31  2738.5 1790.86  2758.5 1784.66
  2768.5 1783.68  2818.5 1782.25  2838.5 1782.19  2858.5 1783.73  2908.5 1783.13
  2938.5 1780.03  2978.5 1779.56  2981.6 1778.50  2982.8 1777.90  5770.3 1778.50
  5850.5 1785.17  5940.7 1787.23  5959.5 1786.50  6131.1 1791.79  6281.5 1793.64
  6301.5 1794.99  6482.0 1798.80  6680.8 1801.63  7023.3 1805.18  7424.0 1806.40
  7444.0 1806.08  7454.0 1803.46  7464.1 1803.43  7469.9 1804.63  7504.6 1804.88
#Mann=5,-1,0
  2686.7    0.05       0  2981.6   0.035       0  5770.3    0.05       0
  6482.0    0.12       0  6680.8    0.05       0
Bank Sta=2981.6,5770.3
Exp/Cntr=0.3,0.1

Type RM Length L Ch R = 1,79775,329,329,329
BEGIN DESCRIPTION:
Mapping XS 7c5be937
END DESCRIPTION:
XS GIS Cut Line= 5
      1585490.00      6824667.99      1586318.14      6824819.03
      1587250.44      6825110.70      1588870.23      6825063.82
      1590203.53      6824511.76
#Sta/Elev= 30
  2322.7 1796.47  2351.9 1794.97  2368.4 1787.94  2398.9 1784.93  2521.9 1782.67
  2642.9 1784.05  2693.7 1781.76  2764.9 1784.50  2793.4 1781.93  2798.5 1784.55
  2815.7 1780.32  2836.0 1778.68  3049.5 1778.50  4141.1 1777.90  5811.5 1778.50
  5845.3 1778.50  5907.7 1782.82  6028.3 1785.40  6105.9 1785.54  6167.5 1789.55
  6254.0 1790.67  6265.5 1794.36  6297.3 1799.58  6466.8 1800.58  6645.8 1801.61
  6994.0 1803.19  7071.1 1805.79  7118.9 1804.26  7195.7 1805.66  7204.9 1803.07
#Mann=7,-1,0
  2322.7    0.05       0  3049.5   0.035       0  5811.5   0.075       0
  5845.3    0.05       0  6028.3    0.05       0  6466.8    0.12       0
  6645.8    0.05       0
Bank Sta=3049.5,5845.3
Exp/Cntr=0.3,0.1

Type RM Length L Ch R = 1,79446,102,102,102
BEGIN DESCRIPTION:
Mapping XS dad88841
END DESCRIPTION:
XS GIS Cut Line= 6
      1585504.75      6824823.37      1585904.08      6824862.44
      1586967.45      6825305.14      1588599.39      6825357.23
      1589141.93      6825292.12      1590244.32      6824766.97
#Sta/Elev= 30
  2137.2 1795.69  2167.6 1795.81  2197.7 1786.30  2227.9 1786.28  2239.5 1787.69
  2308.3 1783.82  2892.0 1778.50  2893.2 1777.90  5599.9 1778.50  5671.3 1783.64
  5701.9 1782.30  5742.6 1784.36  5761.0 1788.70  5812.3 1792.30  5834.4 1791.70
  5844.6 1786.94  5854.8 1784.29  5868.8 1783.16  5944.1 1783.61  6041.6 1783.90
  6136.9 1786.91  6252.0 1790.79  6357.8 1790.86  6373.9 1794.21  6386.0 1798.89
  6873.8 1801.67  6905.5 1803.71  7038.5 1803.37  7061.0 1800.05  7093.1 1802.72
#Mann=5,-1,0
  2137.2    0.05       0  2892.0   0.035       0  5599.9    0.05       0
  5944.1   0.075       0  6136.9    0.05       0
Bank Sta=2892,5599.9
Exp/Cntr=0.3,0.1

Type RM Length L Ch R = 1,79344,254,254,254
BEGIN DESCRIPTION:
Cedar Creek 79344.07
END DESCRIPTION:
XS GIS Cut Line= 4
      1585561.01      6824878.24      1586859.65      6825392.14
      1589095.76      6825482.41      1590199.47      6825072.86
#Sta/Elev= 30
  2157.2 1795.87  2876.7 1795.77  3009.2 1794.73  3014.5 1790.18  3063.2 1794.40
  3068.6 1789.71  3093.0 1794.47  3309.2 1794.18  3338.9 1789.44  3447.1 1794.56
  3476.8 1789.46  3501.1 1794.47  3530.8 1789.33  3574.7 1795.06  4840.2 1791.30
  5550.8 1795.95  5570.8 1791.72  5823.5 1796.77  5897.6 1793.61  5902.1 1783.90
  5903.2 1783.30  5956.0 1783.90  6118.4 1786.02  6243.2 1787.57  6399.0 1789.19
  6430.9 1797.56  6528.4 1798.42  6758.6 1799.71  6944.0 1805.20  6969.0 1801.15
#Mann=7,-1,0
  2157.2    0.05       0  5902.1   0.035       0  5956.0    0.05       0
  6118.4   0.075       0  6243.2    0.05       0  6528.4   0.075       0
  6758.6    0.05       0
Bank Sta=5902.1,5956
Exp/Cntr=0.3,0.1

Type RM Length L Ch R = 1,79090,633,633,633
BEGIN DESCRIPTION:
Cedar Creek 79089.69
END DESCRIPTION:
XS GIS Cut Line= 3
      1585554.08      6824989.35      1587380.48      6825676.86
      1590220.36      6825669.92
#Sta/Elev= 30
  2023.7 1778.11  2208.0 1778.37  2227.6 1781.87  2257.8 1782.49  3542.9 1775.99
  3894.6 1769.10  4083.6 1759.84  4129.7 1753.64  4503.4 1755.52  4869.7 1756.52
  4981.4 1749.43  4982.0 1748.83  5008.4 1749.43  5009.7 1753.37  5039.7 1758.56
  5429.7 1760.97  5554.1 1774.03  5749.7 1785.58  5769.7 1790.55  5829.7 1780.17
  5919.7 1778.72  6089.7 1783.14  6179.7 1782.30  6229.7 1778.15  6329.7 1787.08
  6384.3 1788.98  6493.3 1793.56  6739.7 1793.70  6779.7 1798.34  6815.1 1793.33
#Mann=7,-1,0
  2023.7    0.05       0  4083.6    0.12       0  4503.4    0.05       0
  4981.4   0.035       0  5008.4    0.05       0  6384.3   0.075       0
  6493.3    0.05       0
#XS Ineff=2,0
    0.00 4606.70 1767.47 5393.30    0.00 1767.47
Permanent Ineff=
       F       F
Bank Sta=4981.4,5008.4
Exp/Cntr=0.3,0.1

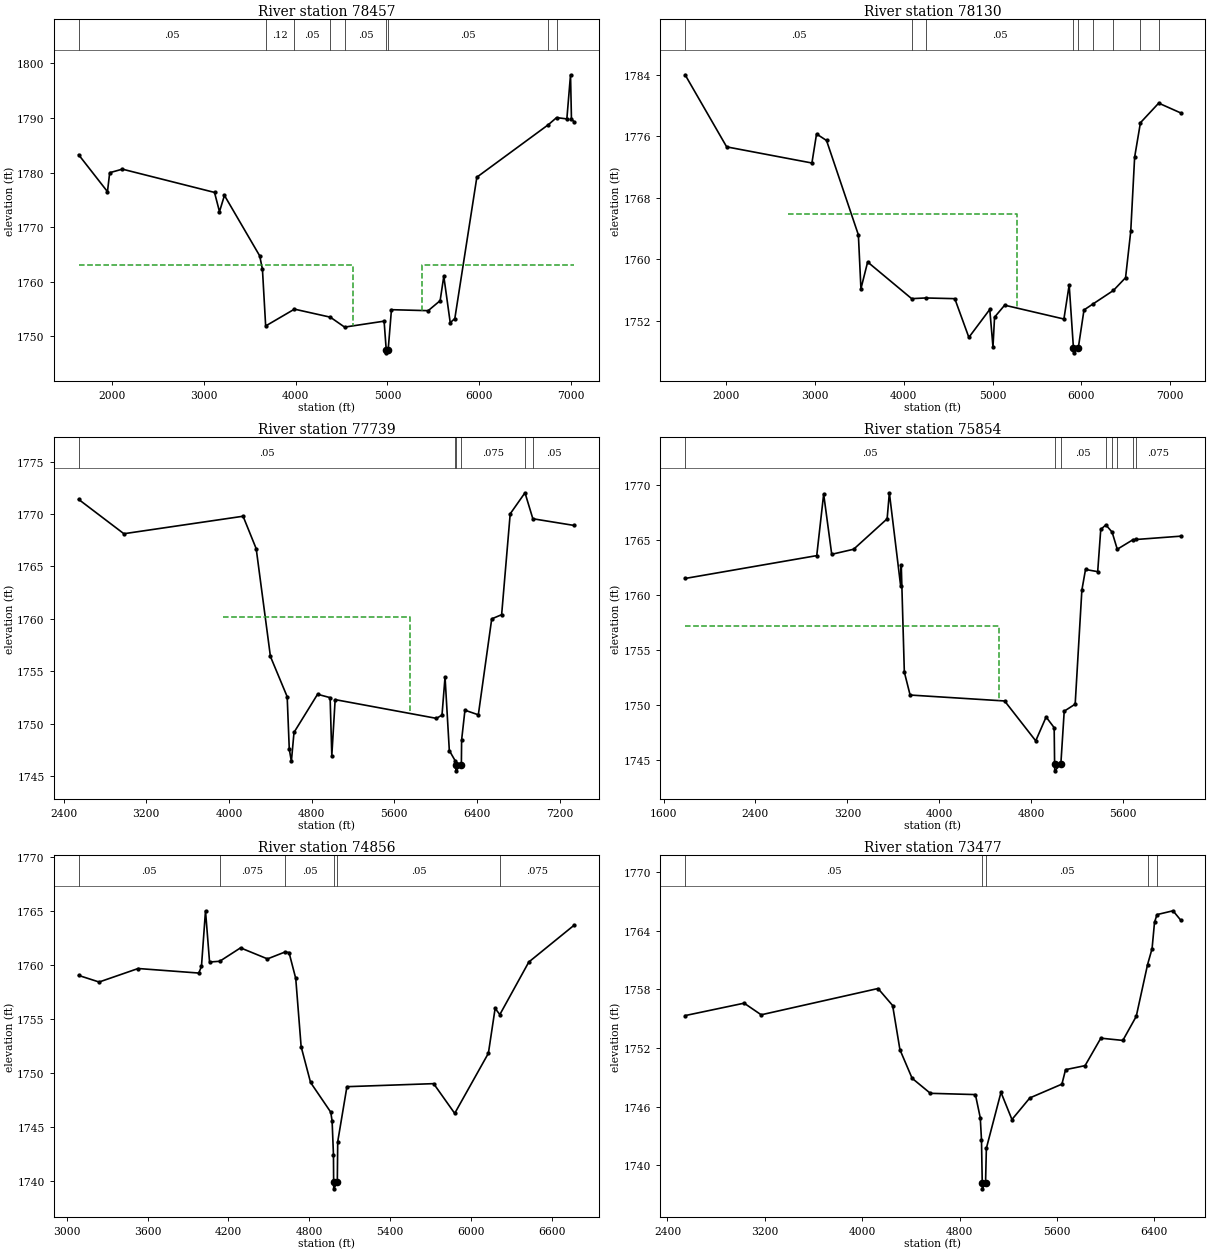
Type RM Length L Ch R = 1,78457,327,327,327
BEGIN DESCRIPTION:
Cedar Creek 78456.51
END DESCRIPTION:
XS GIS Cut Line= 3
      1585547.15      6825037.97      1588324.92      6826135.19
      1590734.65      6826169.91
#Sta/Elev= 30
  1637.1 1783.26  1951.1 1776.50  1975.4 1779.97  2113.4 1780.62  3116.9 1776.36
  3171.0 1772.84  3225.1 1775.81  3609.2 1764.74  3638.9 1762.28  3673.9 1751.91
  3987.3 1754.99  4377.9 1753.52  4533.7 1751.70  4963.8 1752.79  4986.7 1747.59
  4987.2 1746.99  5008.3 1747.59  5043.8 1754.89  5443.9 1754.71  5573.9 1756.54
  5613.9 1761.01  5683.9 1752.51  5733.9 1753.26  5973.9 1779.15  6751.6 1788.75
  6842.2 1790.06  6954.0 1789.82  6994.0 1797.90  7004.0 1789.83  7033.7 1789.26
#Mann=9,-1,0
  1637.1    0.05       0  3673.9    0.12       0  3987.3    0.05       0
  4377.9    0.12       0  4533.7    0.05       0  4986.7   0.035       0
  5008.3    0.05       0  6751.6   0.075       0  6842.2     0.1       0
#XS Ineff=2,0
    0.00 4623.80 1763.11 5376.20    0.00 1763.11
Permanent Ineff=
       F       F
Bank Sta=4986.7,5008.3
Exp/Cntr=0.3,0.1

Type RM Length L Ch R = 1,78130,391,391,391
BEGIN DESCRIPTION:
Cedar Creek 78129.72
END DESCRIPTION:
XS GIS Cut Line= 3
      1585519.34      6825065.74      1588686.03      6826461.58
      1590699.94      6827100.48
#Sta/Elev= 30
  1542.4 1783.98  2009.9 1774.60  2968.7 1772.50  3020.8 1776.28  3133.2 1775.43
  3491.3 1763.15  3520.1 1756.14  3595.5 1759.62  4090.6 1754.85  4247.0 1754.94
  4575.7 1754.85  4734.0 1749.81  4969.2 1753.45  5005.2 1748.56  5023.0 1752.44
  5136.6 1754.00  5803.0 1752.20  5862.3 1756.64  5910.3 1748.40  5911.5 1747.80
  5964.3 1748.40  6028.9 1753.38  6127.6 1754.14  6360.2 1755.92  6496.5 1757.58
  6554.7 1763.61  6598.5 1773.26  6663.6 1777.74  6869.2 1780.29  7115.9 1779.02
#Mann=9,-1,0
  1542.4    0.05       0  4090.6   0.075       0  4247.0    0.05       0
  5910.3   0.035       0  5964.3    0.05       0  6127.6    0.12       0
  6360.2    0.05       0  6663.6   0.075       0  6869.2    0.05       0
#XS Ineff=1,-1
 2695.50 5270.90 1765.85
Permanent Ineff=
       F
Bank Sta=5910.3,5964.3
Exp/Cntr=0.3,0.1

Type RM Length L Ch R = 1,77739,1885,1885,1885
BEGIN DESCRIPTION:
Cedar Creek 77738.93
END DESCRIPTION:
XS GIS Cut Line= 3
      1586123.51      6826392.13      1588554.09      6826794.91
      1590713.83      6827676.87
#Sta/Elev= 30
  2545.1 1771.40  2983.1 1768.12  4136.9 1769.79  4263.9 1766.69  4401.6 1756.40
  4563.7 1752.56  4584.0 1747.56  4604.3 1746.38  4629.9 1749.15  4857.7 1752.79
  4979.3 1752.47  4995.8 1746.94  5028.1 1752.28  6008.9 1750.49  6062.4 1750.81
  6091.8 1754.44  6133.2 1747.42  6188.9 1746.46  6195.8 1746.08  6196.9 1745.48
  6249.8 1746.08  6252.2 1748.42  6284.4 1751.27  6414.0 1750.83  6543.6 1759.99
  6639.6 1760.39  6722.5 1770.02  6865.6 1772.03  6941.8 1769.55  7341.7 1768.91
#Mann=6,-1,0
  2545.1    0.05       0  6188.9   0.075       0  6195.8   0.035       0
  6249.8   0.075       0  6865.6   0.075       0  6941.8    0.05       0
#XS Ineff=1,-1
 3942.70 5753.90 1760.15
Permanent Ineff=
       F
Bank Sta=6195.8,6249.8
Exp/Cntr=0.3,0.1

Type RM Length L Ch R = 1,75854,998,998,998
BEGIN DESCRIPTION:
Cedar Creek 75853.52
END DESCRIPTION:
XS GIS Cut Line= 3
      1586602.73      6827253.25      1589817.98      6827510.19
      1590851.34      6827850.02
#Sta/Elev= 30
  1787.9 1761.49  2933.8 1763.57  2994.0 1769.17  3064.2 1763.69  3254.8 1764.15
  3546.5 1766.92  3565.8 1769.29  3664.4 1760.79  3669.5 1762.70  3696.2 1752.97
  3746.4 1750.88  4569.0 1750.34  4839.9 1746.71  4930.2 1748.88  5000.4 1747.91
  5004.2 1744.58  5005.3 1743.98  5058.4 1744.58  5087.8 1749.41  5183.2 1750.05
  5241.5 1760.43  5273.3 1762.31  5379.2 1762.11  5405.8 1765.95  5450.2 1766.37
  5504.6 1765.71  5549.6 1764.15  5686.7 1765.02  5716.6 1765.04  6101.2 1765.34
#Mann=8,-1,0
  1787.9    0.05       0  5004.2   0.035       0  5058.4    0.05       0
  5450.2   0.075       0  5504.6    0.05       0  5549.6   0.075       0
  5686.7    0.05       0  5716.6   0.075       0
#XS Ineff=2,0
    0.00 4517.20 1757.20               0
Permanent Ineff=
       F       F
Bank Sta=5004.2,5058.4
Exp/Cntr=0.3,0.1

Type RM Length L Ch R = 1,74856,1379,1379,1379
BEGIN DESCRIPTION:
Cedar Creek 74855.72
END DESCRIPTION:
XS GIS Cut Line= 3
      1587192.97      6827933.80      1589116.59      6827975.47
      1590871.74      6827919.97
#Sta/Elev= 30
  3087.7 1759.02  3239.8 1758.41  3529.8 1759.66  3979.9 1759.24  3999.9 1759.85
  4029.9 1765.00  4060.0 1760.26  4135.7 1760.33  4290.0 1761.57  4490.1 1760.55
  4621.1 1761.19  4650.1 1761.14  4700.1 1758.74  4740.1 1752.43  4810.1 1749.12
  4960.2 1746.37  4970.2 1745.54  4980.2 1742.42  4981.5 1739.88  4982.1 1739.28
  5008.7 1739.88  5011.8 1743.64  5080.2 1748.73  5724.1 1749.01  5880.6 1746.26
  6130.7 1751.82  6180.8 1755.97  6215.8 1755.40  6430.9 1760.26  6767.8 1763.67
#Mann=6,-1,0
  3087.7    0.05       0  4135.7   0.075       0  4621.1    0.05       0
  4981.5    0.05       0  5008.7    0.05       0  6215.8   0.075       0
Bank Sta=4981.5,5008.7
Exp/Cntr=0.3,0.1

Type RM Length L Ch R = 1,73477,1188,1188,1188
BEGIN DESCRIPTION:
Cedar Creek 73477.1
END DESCRIPTION:
XS GIS Cut Line= 3
      1587199.97      6828364.36      1589644.37      6828412.97
      1591269.35      6828329.64
#Sta/Elev= 30
  2544.9 1755.31  3030.0 1756.58  3170.1 1755.39  4130.2 1758.08  4250.3 1756.34
  4310.3 1751.82  4410.3 1748.90  4560.3 1747.36  4930.4 1747.23  4970.4 1744.86
  4980.4 1742.62  4986.7 1738.19  4987.2 1737.59  5013.8 1738.19  5020.5 1741.74
  5140.6 1747.46  5230.7 1744.68  5377.8 1746.89  5641.3 1748.30  5671.3 1749.78
  5831.5 1750.19  5961.1 1753.00  6141.9 1752.77  6252.1 1755.23  6345.2 1760.53
  6382.2 1762.16  6402.3 1764.86  6422.9 1765.64  6554.4 1766.03  6616.9 1765.08
#Mann=5,-1,0
  2544.9    0.05       0  4986.7    0.05       0  5013.8    0.05       0
  6345.2   0.075       0  6422.9     0.1       0
Bank Sta=4986.7,5013.8
Exp/Cntr=0.3,0.1

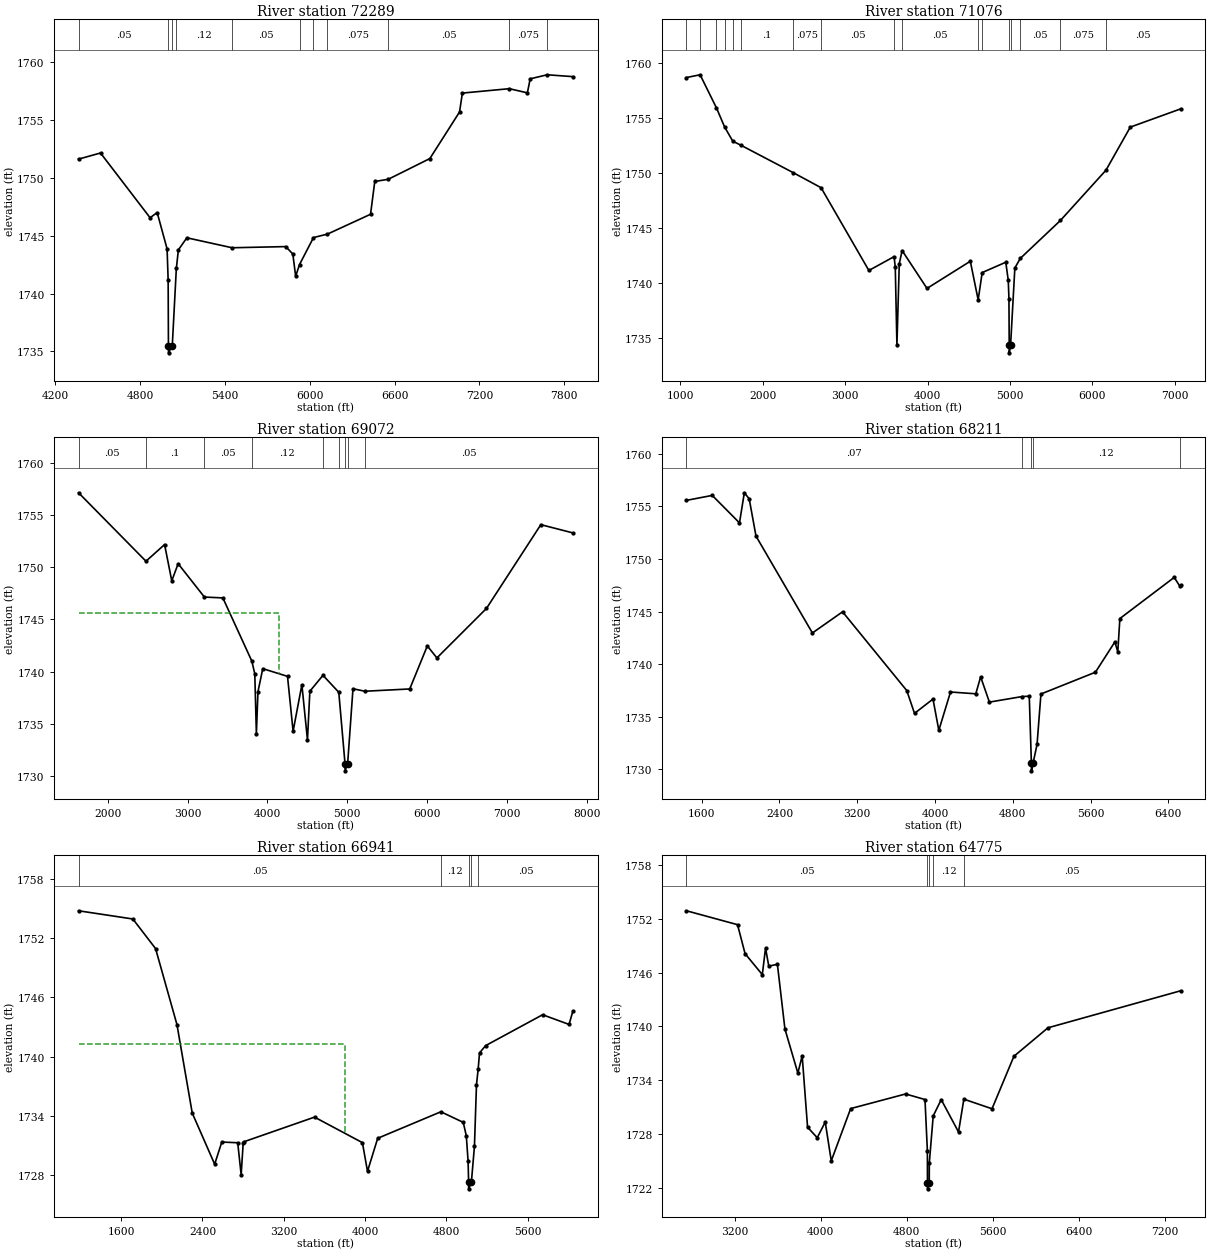
Type RM Length L Ch R = 1,72289,1213,1213,1213
BEGIN DESCRIPTION:
Cedar Creek 72368.85
END DESCRIPTION:
XS GIS Cut Line= 3
      1588620.05      6829275.30      1589255.20      6829319.74
      1592116.58      6829329.64
#Sta/Elev= 30
  4363.3 1751.60  4518.6 1752.13  4869.5 1746.54  4919.6 1746.99  4989.8 1743.85
  4997.4 1741.15  4999.4 1735.48  4999.9 1734.88  5026.5 1735.48  5055.3 1742.16
  5069.8 1743.77  5129.8 1744.81  5449.8 1743.95  5829.8 1744.05  5879.8 1743.41
  5899.8 1741.49  5927.1 1742.50  6026.1 1744.83  6125.1 1745.13  6429.8 1746.84
  6459.8 1749.67  6555.2 1749.86  6849.8 1751.65  7059.8 1755.67  7079.8 1757.30
  7411.8 1757.68  7539.8 1757.32  7559.8 1758.53  7680.0 1758.88  7861.4 1758.72
#Mann=11,-1,0
  4363.3    0.05       0  4999.4    0.05       0  5026.5    0.05       0
  5055.3    0.12       0  5449.8    0.05       0  5927.1    0.12       0
  6026.1    0.05       0  6125.1   0.075       0  6555.2    0.05       0
  7411.8   0.075       0  7680.0    0.05       0
Bank Sta=4999.4,5026.5
Exp/Cntr=0.3,0.1

Type RM Length L Ch R = 1,71076,2004,2004,2004
BEGIN DESCRIPTION:
Cedar Creek 71075.82
END DESCRIPTION:
XS GIS Cut Line= 3
      1586033.27      6830190.75      1589956.87      6830072.69
      1592026.32      6830024.08
#Sta/Elev= 30
  1075.9 1758.66  1241.3 1758.91  1439.6 1755.90  1538.7 1754.16  1637.8 1752.87
  1736.9 1752.50  2370.2 1750.01  2708.7 1748.64  3288.6 1741.11  3594.4 1742.37
  3608.8 1741.42  3628.8 1734.34  3657.4 1741.73  3692.0 1742.92  3993.7 1739.48
  4519.2 1741.95  4614.3 1738.44  4663.3 1740.92  4949.4 1741.86  4979.4 1740.22
  4987.7 1738.56  4991.1 1734.32  4991.5 1733.62  5007.6 1734.32  5059.4 1741.34
  5125.5 1742.21  5612.3 1745.66  6164.5 1750.23  6459.8 1754.15  7071.3 1755.81
#Mann=17,-1,0
  1075.9    0.05       0  1241.3     0.1       0  1439.6   0.075       0
  1538.7    0.05       0  1637.8   0.075       0  1736.9     0.1       0
  2370.2   0.075       0  2708.7    0.05       0  3594.4    0.12       0
  3692.0    0.05       0  4614.3    0.12       0  4663.3    0.05       0
  4991.1    0.05       0  5007.6    0.05       0  5125.5    0.05       0
  5612.3   0.075       0  6164.5    0.05       0
Bank Sta=4991.1,5007.6
Exp/Cntr=0.3,0.1

Type RM Length L Ch R = 1,69072,861,861,861
BEGIN DESCRIPTION:
Cedar Creek 69071.737
END DESCRIPTION:
XS GIS Cut Line= 3
      1585887.40      6830975.47      1589252.32      6830932.52
      1592074.88      6830774.08
#Sta/Elev= 30
  1634.8 1757.16  2479.2 1750.59  2712.5 1752.19  2802.5 1748.71  2882.5 1750.35
  3211.5 1747.15  3442.6 1747.07  3805.7 1741.00  3842.6 1739.79  3862.6 1734.04
  3882.6 1738.07  3942.6 1740.28  4252.6 1739.54  4322.6 1734.27  4432.6 1738.73
  4502.6 1733.44  4532.6 1738.11  4697.0 1739.64  4895.0 1738.01  4973.1 1731.17
  4973.8 1730.47  5006.1 1731.17  5072.8 1738.35  5222.3 1738.11  5783.9 1738.33
  6004.3 1742.46  6124.4 1741.31  6745.4 1746.06  7426.5 1754.10  7827.0 1753.31
#Mann=9,-1,0
  1634.8    0.05       0  2479.2     0.1       0  3211.5    0.05       0
  3805.7    0.12       0  4697.0     0.1       0  4895.0    0.12       0
  4973.1    0.07       0  5006.1    0.12       0  5222.3    0.05       0
#XS Ineff=2,0
    0.00 4143.70 1745.61               0
Permanent Ineff=
       F       F
Bank Sta=4973.1,5006.1
Exp/Cntr=0.3,0.1

Type RM Length L Ch R = 1,68211,1270,1270,1270
BEGIN DESCRIPTION:
Cedar Creek 67878.998
END DESCRIPTION:
XS GIS Cut Line= 3
      1585949.91      6831537.97      1589505.72      6831603.06
      1591031.66      6831551.91
#Sta/Elev= 30
  1443.6 1755.57  1708.7 1756.04  1988.8 1753.43  2038.8 1756.29  2088.8 1755.72
  2158.8 1752.17  2738.9 1742.97  3049.0 1744.98  3709.1 1737.50  3789.1 1735.33
  3979.1 1736.69  4039.1 1733.72  4159.1 1737.36  4419.2 1737.19  4469.2 1738.80
  4559.2 1736.40  4896.8 1736.93  4969.3 1736.96  4991.2 1730.57  4991.6 1729.87
  5007.7 1730.57  5049.3 1732.38  5089.3 1737.17  5649.6 1739.24  5849.8 1742.12
  5879.8 1741.17  5901.1 1744.34  6460.1 1748.25  6518.1 1747.41  6526.8 1747.50
#Mann=5,-1,0
  1443.6    0.07       0  4896.8    0.12       0  4991.2    0.07       0
  5007.7    0.12       0  6518.1    0.12       0
Bank Sta=4991.2,5007.7
Exp/Cntr=0.3,0.1

Type RM Length L Ch R = 1,66941,2166,2166,2166
BEGIN DESCRIPTION:
Cedar Creek 66941.39
END DESCRIPTION:
XS GIS Cut Line= 3
      1585519.36      6832954.64      1589088.81      6832676.86
      1590371.80      6832607.51
#Sta/Elev= 30
  1180.5 1754.74  1714.9 1753.91  1938.4 1750.92  2149.1 1743.23  2299.5 1734.29
  2520.2 1729.12  2590.4 1731.36  2747.1 1731.29  2781.0 1728.06  2801.0 1731.26
  2811.1 1731.40  3503.1 1733.88  3974.6 1731.30  4024.7 1728.40  4125.0 1731.74
  4747.0 1734.42  4967.2 1733.35  4997.3 1731.99  5014.9 1729.40  5019.9 1727.33
  5020.5 1726.63  5047.5 1727.33  5077.4 1730.93  5097.4 1737.14  5114.0 1738.74
  5127.5 1740.37  5187.6 1741.11  5748.4 1744.23  6008.7 1743.25  6045.6 1744.57
#Mann=5,-1,0
  1180.5    0.05       0  4747.0    0.12       0  5019.9    0.07       0
  5047.5    0.12       0  5114.0    0.05       0
#XS Ineff=2,0
    0.00 3800.00 1741.32 6521.20    0.00 1741.32
Permanent Ineff=
       F       F
Bank Sta=5019.9,5047.5
Exp/Cntr=0.3,0.1

Type RM Length L Ch R = 1,64775,1853,1853,1853
BEGIN DESCRIPTION:
Cedar Creek 64775.27
END DESCRIPTION:
XS GIS Cut Line= 4
      1585811.05      6833412.97      1588047.15      6833343.53
      1588594.55      6833289.60      1590304.06      6832718.54
#Sta/Elev= 30
  2753.8 1752.89  3228.0 1751.34  3298.0 1748.11  3458.1 1745.77  3488.1 1748.73
  3518.1 1746.72  3598.2 1746.92  3668.2 1739.70  3788.3 1734.79  3828.3 1736.71
  3878.3 1728.75  3968.3 1727.58  4042.4 1729.33  4098.4 1725.00  4278.5 1730.83
  4788.7 1732.46  4968.8 1731.84  4991.0 1726.10  4991.8 1722.58  4992.1 1721.88
  5008.3 1722.58  5008.9 1724.78  5045.1 1730.01  5119.5 1731.83  5280.2 1728.22
  5329.6 1731.88  5591.2 1730.81  5794.5 1736.66  6110.8 1739.84  7343.4 1743.97
#Mann=5,-1,0
  2753.8    0.05       0  4991.8    0.04       0  5008.3    0.05       0
  5045.1    0.12       0  5329.6    0.05       0
Bank Sta=4991.8,5008.3
Exp/Cntr=0.3,0.1

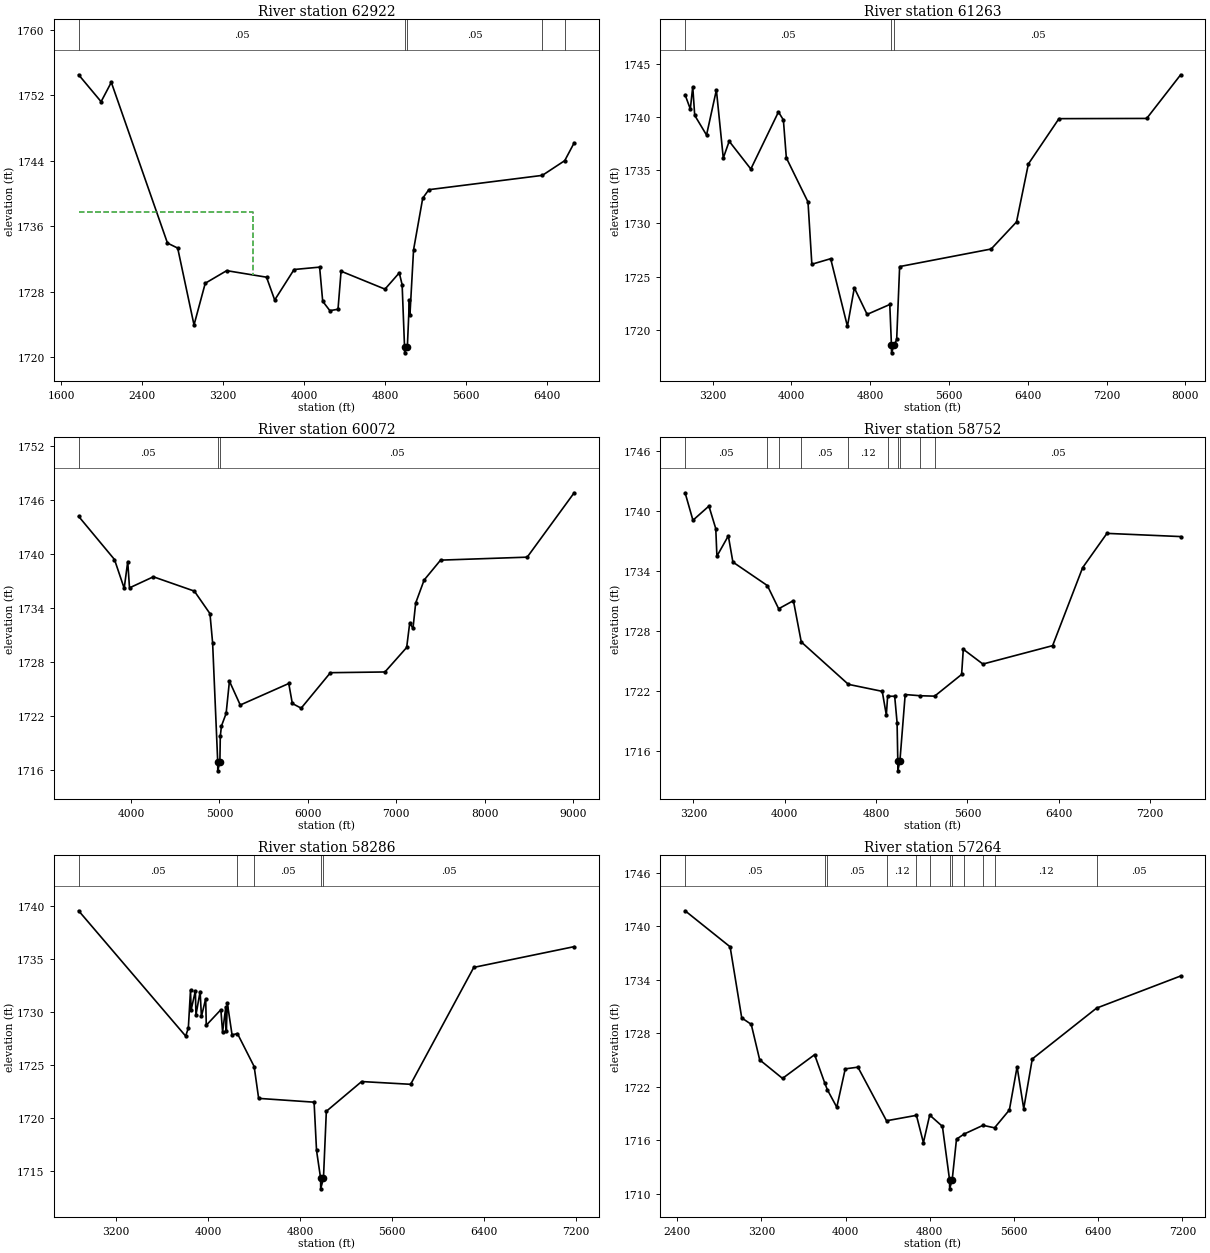
Type RM Length L Ch R = 1,62922,1659,1659,1659
BEGIN DESCRIPTION:
Cedar Creek 62820.034
END DESCRIPTION:
XS GIS Cut Line= 3
      1585904.99      6833688.00      1589109.65      6834107.41
      1590761.17      6833920.06
#Sta/Elev= 30
  1772.2 1754.50  1994.1 1751.21  2094.9 1753.58  2649.6 1733.92  2750.5 1733.31
  2911.8 1723.91  3022.8 1729.01  3234.6 1730.55  3627.9 1729.75  3708.6 1726.96
  3900.2 1730.69  4152.3 1730.98  4182.6 1726.81  4253.2 1725.66  4333.9 1725.83
  4364.1 1730.48  4797.8 1728.29  4939.0 1730.28  4967.2 1728.83  4991.0 1721.20
  4991.6 1720.50  5018.6 1721.20  5039.0 1726.97  5044.1 1725.09  5080.0 1733.09
  5170.6 1739.41  5231.0 1740.45  6351.8 1742.20  6573.0 1744.00  6666.3 1746.18
#Mann=5,-1,0
  1772.2    0.05       0  4991.0   0.035       0  5018.6    0.05       0
  6351.8   0.075       0  6573.0    0.05       0
#XS Ineff=2,0
    0.00 3493.60 1737.75               0
Permanent Ineff=
       F       F
Bank Sta=4991,5018.6
Exp/Cntr=0.3,0.1

Type RM Length L Ch R = 1,61263,1191,1191,1191
BEGIN DESCRIPTION:
Cedar Creek 61308.65
END DESCRIPTION:
XS GIS Cut Line= 3
      1585887.45      6834892.14      1588894.37      6834940.75
      1590734.60      6834100.49
#Sta/Elev= 30
  2920.6 1742.07  2973.6 1740.73  2998.2 1742.83  3018.2 1740.14  3138.2 1738.29
  3238.2 1742.52  3308.2 1736.13  3368.2 1737.71  3587.9 1735.10  3868.3 1740.46
  3918.3 1739.71  3948.3 1736.15  4168.3 1732.00  4207.3 1726.16  4398.3 1726.68
  4568.4 1720.33  4638.4 1723.94  4768.4 1721.45  4998.4 1722.38  5015.4 1718.54
  5016.0 1717.84  5043.1 1718.54  5068.4 1719.10  5098.4 1725.94  6027.5 1727.59
  6284.8 1730.13  6405.4 1735.58  6715.8 1739.83  7606.4 1739.85  7950.9 1743.95
#Mann=3,-1,0
  2920.6    0.05       0  5015.4   0.035       0  5043.1    0.05       0
Bank Sta=5015.4,5043.1
Exp/Cntr=0.3,0.1

Type RM Length L Ch R = 1,60072,1320,1320,1320
BEGIN DESCRIPTION:
Cedar Creek 60071.7
END DESCRIPTION:
XS GIS Cut Line= 4
      1585609.62      6835406.03      1587213.81      6835426.86
      1588540.20      6835343.53      1590894.35      6834079.64
#Sta/Elev= 30
  3407.7 1744.13  3813.1 1739.34  3923.1 1736.14  3963.1 1739.11  3983.1 1736.19
  4253.1 1737.42  4716.5 1735.83  4893.2 1733.33  4923.2 1730.09  4981.0 1716.87
  4981.6 1715.87  5005.6 1716.87  5010.1 1719.72  5023.2 1720.85  5076.0 1722.24
  5113.4 1725.83  5235.9 1723.18  5784.7 1725.57  5824.8 1723.35  5925.0 1722.83
  6255.7 1726.77  6872.5 1726.85  7118.3 1729.57  7152.3 1732.25  7189.9 1731.72
  7220.4 1734.51  7315.8 1737.06  7501.7 1739.27  8481.7 1739.60  9013.0 1746.75
#Mann=3,-1,0
  3407.7    0.05       0  4981.0   0.035       0  5005.6    0.05       0
Bank Sta=4981,5005.6
Exp/Cntr=0.3,0.1

Type RM Length L Ch R = 1,58752,466,466,466
BEGIN DESCRIPTION:
Mapping XS aeceeb58
END DESCRIPTION:
XS GIS Cut Line= 4
      1586196.27      6836350.06      1587515.74      6836358.74
      1588644.21      6835542.77      1590210.53      6835095.87
#Sta/Elev= 30
  3127.1 1741.84  3195.8 1739.09  3335.8 1740.51  3395.8 1738.25  3405.8 1735.50
  3505.8 1737.53  3545.8 1734.91  3847.7 1732.56  3946.7 1730.24  4075.9 1731.05
  4144.7 1726.92  4557.4 1722.68  4854.0 1721.98  4889.9 1719.61  4901.3 1721.49
  4963.1 1721.49  4984.0 1718.86  4990.4 1715.03  4990.8 1714.03  5008.9 1715.03
  5055.1 1721.66  5188.4 1721.54  5313.1 1721.50  5549.4 1723.67  5564.1 1726.19
  5735.8 1724.71  6346.5 1726.55  6609.5 1734.35  6822.5 1737.78  7468.0 1737.46
#Mann=10,-1,0
  3127.1    0.05       0  3847.7   0.075       0  3946.7     0.1       0
  4144.7    0.05       0  4557.4    0.12       0  4901.3    0.05       0
  4990.4    0.05       0  5008.9    0.05       0  5188.4    0.12       0
  5313.1    0.05       0
Bank Sta=4990.4,5008.9
Exp/Cntr=0.3,0.1

Type RM Length L Ch R = 1,58286,1022,1022,1022
BEGIN DESCRIPTION:
Mapping XS 923ba115
END DESCRIPTION:
XS GIS Cut Line= 5
      1586356.84      6836957.71      1587880.32      6836597.45
      1588835.18      6835876.97      1589264.87      6835633.91
      1590315.19      6835551.45
#Sta/Elev= 30
  2875.1 1739.59  3805.6 1727.75  3828.9 1728.49  3847.9 1732.09  3853.1 1730.21
  3890.2 1732.02  3895.3 1729.75  3931.6 1731.96  3942.8 1729.60  3979.9 1731.28
  3985.0 1728.77  4111.9 1730.24  4126.9 1728.13  4154.2 1730.45  4159.3 1728.23
  4168.0 1730.87  4209.1 1727.87  4256.2 1727.98  4401.3 1724.87  4440.4 1721.86
  4922.5 1721.50  4943.7 1716.94  4979.2 1714.31  4979.8 1713.31  5004.0 1714.31
  5029.0 1720.64  5335.9 1723.45  5762.0 1723.19  6311.1 1734.24  7184.0 1736.20
#Mann=5,-1,0
  2875.1    0.05       0  4256.2   0.075       0  4401.3    0.05       0
  4979.2    0.04       0  5004.0    0.05       0
Bank Sta=4979.2,5004
Exp/Cntr=0.3,0.1

Type RM Length L Ch R = 1,57264,425,425,425
BEGIN DESCRIPTION:
Cedar Creek 57264.32
END DESCRIPTION:
XS GIS Cut Line= 3
      1586338.79      6837301.86      1588859.65      6837086.58
      1590936.02      6836426.86
#Sta/Elev= 30
  2474.3 1741.72  2902.1 1737.68  3012.5 1729.71  3102.8 1728.99  3183.1 1725.01
  3400.0 1722.93  3705.0 1725.59  3799.6 1722.47  3826.0 1721.66  3915.7 1719.70
  3996.0 1724.00  4116.5 1724.19  4388.1 1718.18  4672.4 1718.79  4738.7 1715.73
  4798.5 1718.82  4919.4 1717.55  4987.4 1711.55  4988.0 1710.55  5012.2 1711.55
  5053.2 1716.12  5126.7 1716.70  5305.1 1717.67  5414.8 1717.39  5555.6 1719.39
  5629.0 1724.23  5692.0 1719.54  5773.2 1725.11  6384.3 1730.81  7183.0 1734.41
#Mann=12,-1,0
  2474.3    0.05       0  3799.6     0.1       0  3826.0    0.05       0
  4388.1    0.12       0  4672.4    0.05       0  4798.5    0.12       0
  4987.4    0.05       0  5012.2    0.12       0  5126.7    0.12       0
  5305.1    0.05       0  5414.8    0.12       0  6384.3    0.05       0
Bank Sta=4987.4,5012.2
Exp/Cntr=0.3,0.1