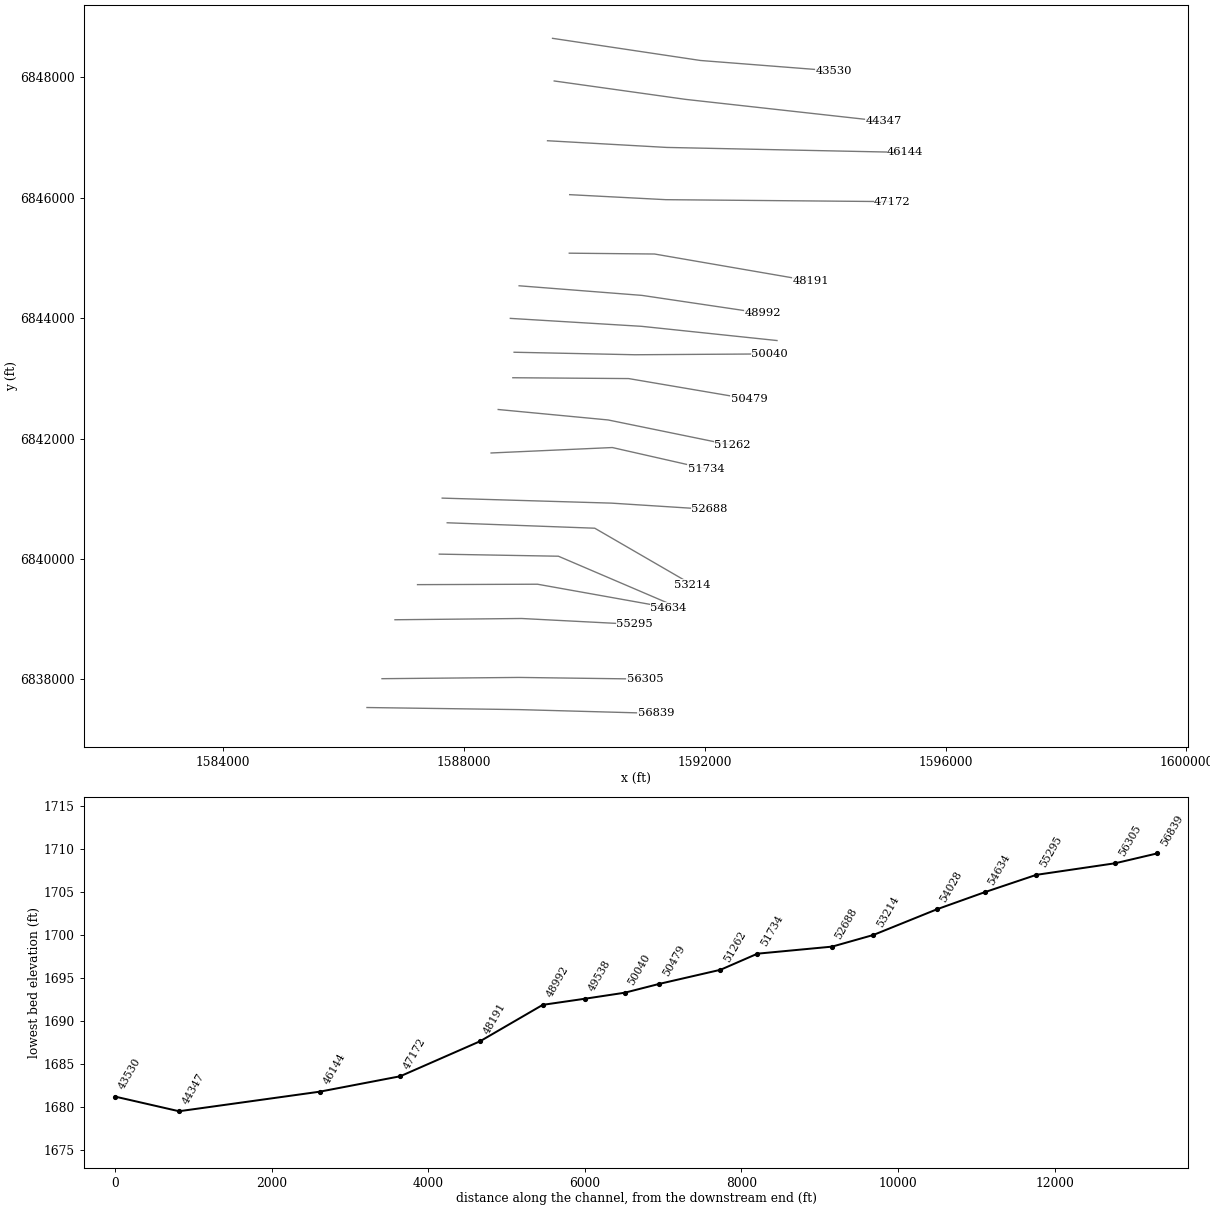
HEC-RAS study Cedar Creek.prj: Cedar Creek Base Level Engineering

--- Cedar Creek.g01 (geometry) --- (continued)

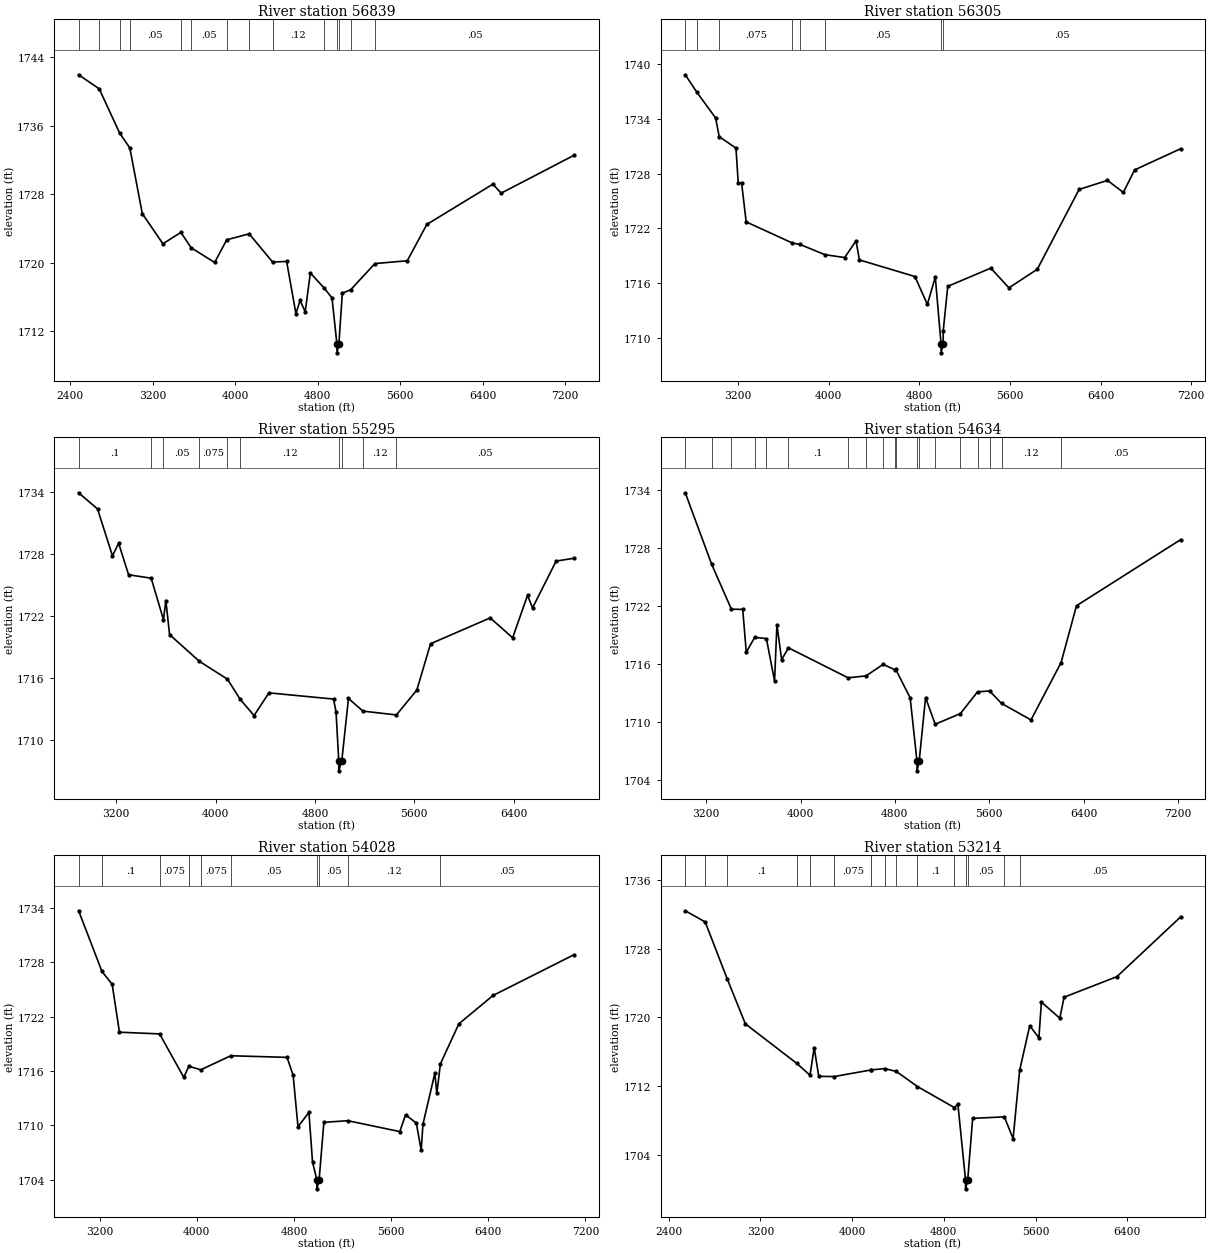
Type RM Length L Ch R = 1,56839,534,534,534
BEGIN DESCRIPTION:
Cedar Creek 56839.24
END DESCRIPTION:
XS GIS Cut Line= 3
      1586387.38      6837531.03      1588922.15      6837496.30
      1591191.48      6837433.84
#Sta/Elev= 30
  2481.9 1741.94  2681.6 1740.30  2879.7 1735.14  2978.7 1733.39  3099.6 1725.73
  3299.6 1722.21  3473.9 1723.54  3573.0 1721.75  3801.3 1720.03  3918.9 1722.68
  4136.4 1723.37  4363.5 1720.08  4499.7 1720.15  4589.7 1714.05  4629.7 1715.59
  4679.7 1714.28  4729.7 1718.80  4860.5 1717.09  4939.8 1715.89  4987.6 1710.48
  4988.1 1709.48  5006.2 1710.48  5039.8 1716.43  5121.8 1716.86  5355.9 1719.90
  5670.0 1720.23  5859.5 1724.47  6500.3 1729.17  6580.4 1728.12  7287.1 1732.54
#Mann=14,-1,0
  2481.9     0.1       0  2681.6    0.05       0  2879.7   0.075       0
  2978.7    0.05       0  3473.9   0.075       0  3573.0    0.05       0
  3918.9   0.075       0  4136.4    0.05       0  4363.5    0.12       0
  4860.5    0.05       0  4987.6   0.035       0  5006.2    0.05       0
  5121.8    0.12       0  5355.9    0.05       0
Bank Sta=4987.6,5006.2
Exp/Cntr=0.3,0.1

Type RM Length L Ch R = 1,56305,1010,1010,1010
BEGIN DESCRIPTION:
Cedar Creek 56304.84
END DESCRIPTION:
XS GIS Cut Line= 3
      1586637.46      6838010.19      1588915.20      6838031.03
      1591011.18      6838003.26
#Sta/Elev= 30
  2732.2 1738.83  2834.3 1736.92  2999.8 1734.10  3032.0 1732.04  3179.8 1730.79
  3199.8 1726.98  3229.8 1726.95  3269.8 1722.70  3678.2 1720.38  3746.3 1720.22
  3966.1 1719.10  4139.8 1718.79  4239.8 1720.62  4269.8 1718.53  4759.8 1716.71
  4869.8 1713.65  4939.8 1716.66  4990.6 1709.34  4991.1 1708.34  5009.3 1709.34
  5010.0 1710.76  5049.8 1715.63  5429.9 1717.63  5589.9 1715.47  5839.9 1717.50
  6209.9 1726.26  6460.0 1727.25  6600.0 1725.93  6700.0 1728.40  7106.2 1730.72
#Mann=8,-1,0
  2732.2   0.075       0  2834.3     0.1       0  3032.0   0.075       0
  3678.2    0.05       0  3746.3   0.075       0  3966.1    0.05       0
  4990.6   0.035       0  5009.3    0.05       0
Bank Sta=4990.6,5009.3
Exp/Cntr=0.3,0.1

Type RM Length L Ch R = 1,55295,661,661,661
BEGIN DESCRIPTION:
Cedar Creek 55294.71
END DESCRIPTION:
XS GIS Cut Line= 3
      1586852.70      6838989.36      1588956.87      6839010.19
      1590838.49      6838912.99
#Sta/Elev= 30
  2897.2 1733.95  3049.5 1732.38  3169.5 1727.84  3219.5 1729.05  3299.5 1726.00
  3481.5 1725.67  3580.5 1721.64  3599.5 1723.50  3629.5 1720.20  3870.3 1717.60
  4095.3 1715.88  4197.7 1713.93  4309.6 1712.35  4429.6 1714.55  4949.6 1713.95
  4969.6 1712.73  4991.4 1707.99  4992.0 1706.99  5016.3 1707.99  5069.7 1714.01
  5186.3 1712.78  5455.9 1712.41  5620.4 1714.83  5730.6 1719.31  6211.2 1721.82
  6391.5 1719.89  6511.6 1724.00  6551.7 1722.79  6741.9 1727.33  6885.6 1727.60
#Mann=10,-1,0
  2897.2     0.1       0  3481.5   0.075       0  3580.5    0.05       0
  3870.3   0.075       0  4095.3    0.05       0  4197.7    0.12       0
  4991.4    0.05       0  5016.3    0.12       0  5186.3    0.12       0
  5455.9    0.05       0
Bank Sta=4991.4,5016.3
Exp/Cntr=0.3,0.1

Type RM Length L Ch R = 1,54634,606,606,606
BEGIN DESCRIPTION:
Cedar Creek 54633.55
END DESCRIPTION:
XS GIS Cut Line= 3
      1587227.71      6839572.69      1589220.76      6839579.64
      1591394.38      6839190.75
#Sta/Elev= 30
  3022.6 1733.75  3245.4 1726.38  3413.6 1721.70  3509.9 1721.68  3539.9 1717.24
  3611.6 1718.79  3710.6 1718.66  3779.9 1714.26  3799.9 1720.10  3839.9 1716.48
  3897.8 1717.70  4403.5 1714.60  4556.4 1714.80  4700.4 1715.99  4799.4 1715.44
  4807.1 1715.48  4929.9 1712.52  4987.6 1705.97  4988.1 1704.97  5006.3 1705.97
  5060.6 1712.56  5141.9 1709.79  5356.2 1710.90  5501.0 1713.14  5603.4 1713.24
  5704.5 1711.95  5954.6 1710.24  6209.8 1716.18  6340.6 1722.06  7223.8 1728.90
#Mann=19,-1,0
  3022.6    0.05       0  3245.4   0.075       0  3413.6     0.1       0
  3611.6   0.075       0  3710.6    0.05       0  3897.8     0.1       0
  4403.5   0.075       0  4556.4    0.05       0  4700.4    0.12       0
  4799.4    0.05       0  4807.1    0.12       0  4987.6    0.07       0
  5006.3    0.12       0  5141.9    0.12       0  5356.2     0.1       0
  5501.0    0.12       0  5603.4    0.05       0  5704.5    0.12       0
  6209.8    0.05       0
Bank Sta=4987.6,5006.3
Exp/Cntr=0.3,0.1

Type RM Length L Ch R = 1,54028,814,814,814
BEGIN DESCRIPTION:
Cedar Creek 54028.21
END DESCRIPTION:
XS GIS Cut Line= 3
      1587588.81      6840079.64      1589567.98      6840044.91
      1591498.56      6839218.51
#Sta/Elev= 30
  3026.8 1733.69  3219.1 1726.99  3303.0 1725.58  3363.0 1720.29  3693.7 1720.10
  3893.1 1715.30  3934.1 1716.53  4033.2 1716.14  4279.6 1717.69  4743.3 1717.51
  4793.3 1715.54  4833.3 1709.85  4923.3 1711.44  4953.3 1705.93  4988.6 1704.00
  4989.1 1703.00  5007.4 1704.00  5046.5 1710.34  5243.4 1710.52  5671.9 1709.32
  5719.1 1711.17  5808.0 1710.26  5847.9 1707.25  5862.4 1710.13  5960.3 1715.76
  5976.7 1713.53  6006.3 1716.80  6158.1 1721.21  6439.3 1724.34  7106.3 1728.84
#Mann=10,-1,0
  3026.8    0.05       0  3219.1     0.1       0  3693.7   0.075       0
  3934.1    0.05       0  4033.2   0.075       0  4279.6    0.05       0
  4988.6    0.05       0  5007.4    0.05       0  5243.4    0.12       0
  6006.3    0.05       0
Bank Sta=4988.6,5007.4
Exp/Cntr=0.3,0.1

Type RM Length L Ch R = 1,53214,526,526,526
BEGIN DESCRIPTION:
Cedar Creek 53214.36
END DESCRIPTION:
XS GIS Cut Line= 3
      1587720.75      6840600.47      1590172.15      6840510.19
      1591789.86      6839572.89
#Sta/Elev= 30
  2543.7 1732.41  2717.5 1731.11  2908.6 1724.51  3068.3 1719.23  3517.4 1714.62
  3631.9 1713.25  3668.7 1716.44  3708.7 1713.12  3841.6 1713.09  4167.6 1713.87
  4167.9 1713.87  4284.6 1714.02  4385.4 1713.69  4569.6 1711.93  4891.8 1709.48
  4922.5 1709.89  4989.4 1701.01  4989.8 1700.01  5008.1 1701.01  5051.5 1708.22
  5327.8 1708.40  5404.4 1705.86  5461.5 1713.82  5549.4 1719.01  5629.7 1717.61
  5651.2 1721.77  5811.9 1719.89  5849.2 1722.34  6309.7 1724.73  6866.4 1731.70
#Mann=16,-1,0
  2543.7    0.05       0  2717.5   0.075       0  2908.6     0.1       0
  3517.4   0.075       0  3631.9    0.05       0  3841.6   0.075       0
  4167.6     0.1       0  4167.9   0.075       0  4284.6     0.1       0
  4385.4   0.075       0  4569.6     0.1       0  4891.8    0.05       0
  4989.4   0.035       0  5008.1    0.05       0  5327.8    0.12       0
  5461.5    0.05       0
Bank Sta=4989.4,5008.1
Exp/Cntr=0.3,0.1

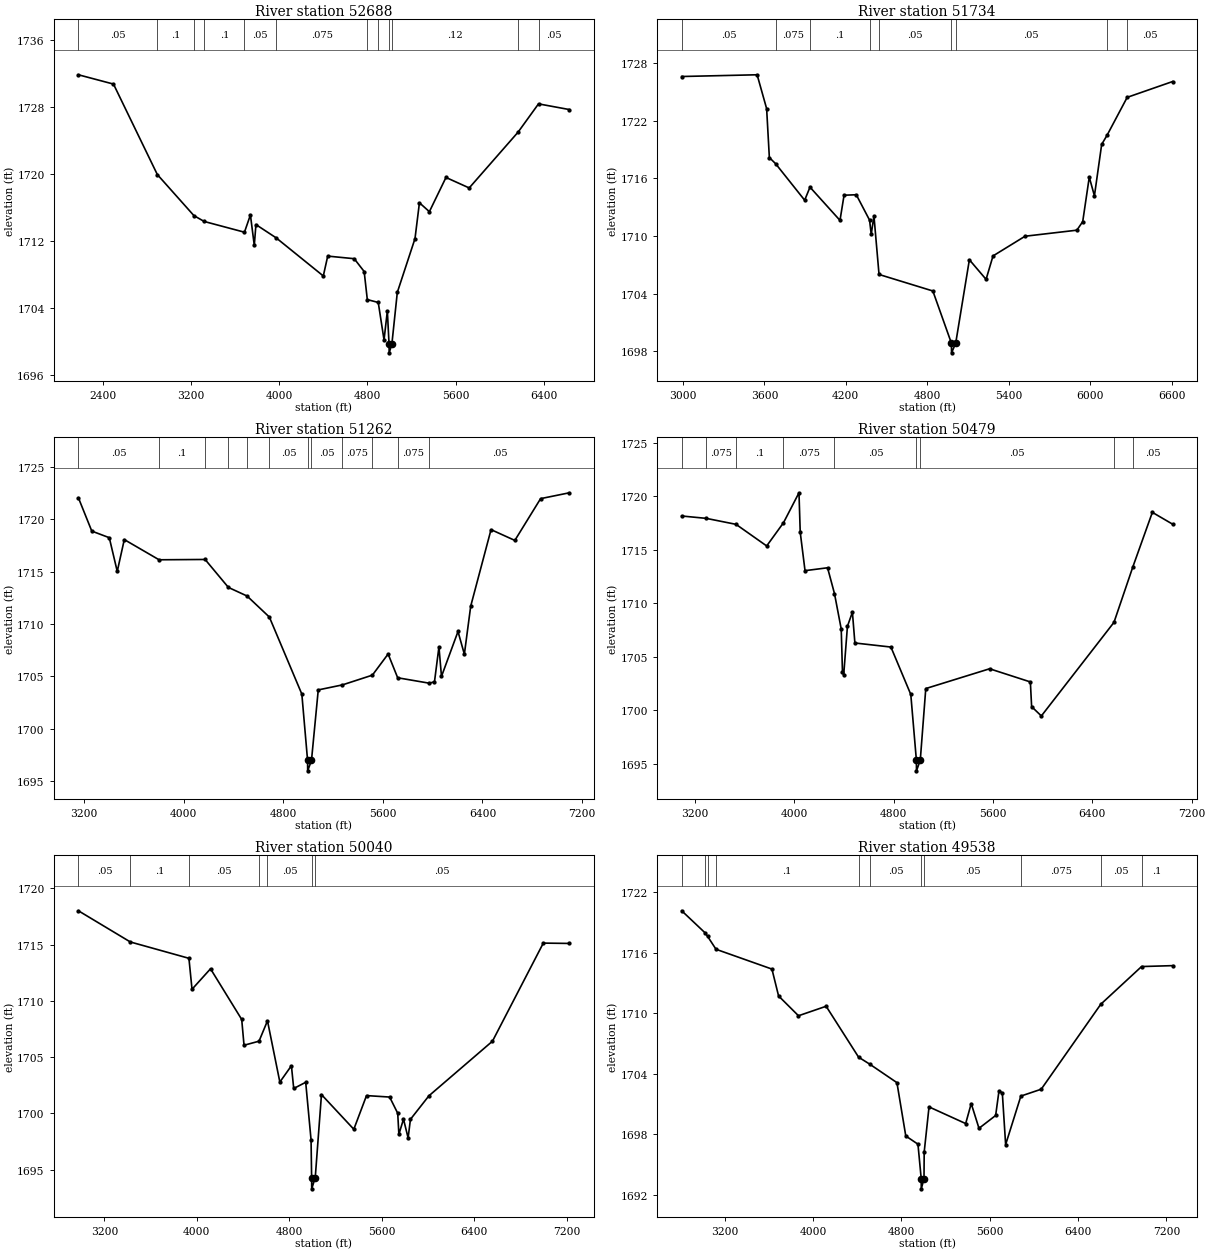
Type RM Length L Ch R = 1,52688,954,954,954
BEGIN DESCRIPTION:
Cedar Creek 52688.23
END DESCRIPTION:
XS GIS Cut Line= 3
      1587637.38      6841010.19      1590449.92      6840926.86
      1592080.93      6840822.75
#Sta/Elev= 30
  2181.1 1731.83  2498.9 1730.72  2896.0 1719.93  3227.5 1715.03  3321.0 1714.33
  3685.4 1713.05  3739.4 1715.11  3774.5 1711.48  3789.4 1713.96  3972.2 1712.38
  4399.7 1707.83  4439.7 1710.20  4679.8 1709.89  4769.9 1708.36  4798.4 1705.01
  4897.5 1704.67  4949.9 1700.20  4979.9 1703.67  4995.5 1699.66  4996.1 1698.66
  5020.5 1699.66  5070.1 1705.87  5230.4 1712.29  5270.5 1716.56  5360.7 1715.50
  5511.0 1719.58  5721.4 1718.33  6164.4 1724.99  6349.3 1728.36  6629.2 1727.68
#Mann=12,-1,0
  2181.1    0.05       0  2896.0     0.1       0  3227.5   0.075       0
  3321.0     0.1       0  3685.4    0.05       0  3972.2   0.075       0
  4798.4    0.05       0  4897.5    0.12       0  4995.5   0.035       0
  5020.5    0.12       0  6164.4    0.12       0  6349.3    0.05       0
Bank Sta=4995.5,5020.5
Exp/Cntr=0.3,0.1

Type RM Length L Ch R = 1,51734,472,472,472
BEGIN DESCRIPTION:
Cedar Creek 51734.01
END DESCRIPTION:
XS GIS Cut Line= 3
      1588449.87      6841760.19      1590463.81      6841850.47
      1592026.31      6841496.30
#Sta/Elev= 30
  2990.8 1726.61  3546.5 1726.79  3616.6 1723.26  3636.6 1718.17  3682.2 1717.54
  3896.8 1713.73  3936.0 1715.09  4157.1 1711.63  4187.1 1714.25  4277.2 1714.30
  4375.0 1711.66  4387.3 1710.17  4407.3 1712.10  4444.8 1706.00  4841.4 1704.28
  4978.3 1698.84  4979.1 1697.84  5009.7 1698.84  5110.5 1707.53  5233.6 1705.49
  5284.8 1707.93  5520.7 1709.98  5902.6 1710.61  5945.7 1711.50  5994.0 1716.13
  6032.0 1714.19  6085.4 1719.54  6125.0 1720.49  6273.4 1724.44  6608.9 1726.09
#Mann=9,-1,0
  2990.8    0.05       0  3682.2   0.075       0  3936.0     0.1       0
  4375.0   0.075       0  4444.8    0.05       0  4978.3   0.035       0
  5009.7    0.05       0  6125.0    0.12       0  6273.4    0.05       0
Bank Sta=4978.3,5009.7
Exp/Cntr=0.3,0.1

Type RM Length L Ch R = 1,51262,783,783,783
BEGIN DESCRIPTION:
Cedar Creek 51262.35
END DESCRIPTION:
XS GIS Cut Line= 3
      1588567.99      6842482.41      1590394.37      6842308.80
      1592461.88      6841885.59
#Sta/Elev= 30
  3153.3 1722.05  3260.8 1718.87  3401.4 1718.24  3465.4 1715.02  3522.0 1718.06
  3801.4 1716.13  4171.3 1716.16  4358.4 1713.49  4508.2 1712.67  4687.5 1710.66
  4948.5 1703.30  4994.6 1696.97  4995.4 1695.97  5026.0 1696.97  5080.4 1703.70
  5274.8 1704.18  5515.2 1705.11  5641.8 1707.13  5718.5 1704.86  5973.1 1704.34
  6014.3 1704.48  6050.1 1707.81  6070.5 1704.99  6203.2 1709.28  6254.3 1707.11
  6305.3 1711.70  6468.6 1719.01  6659.9 1717.98  6866.8 1721.97  7098.3 1722.53
#Mann=12,-1,0
  3153.3    0.05       0  3801.4     0.1       0  4171.3   0.075       0
  4358.4     0.1       0  4508.2   0.075       0  4687.5    0.05       0
  4994.6    0.04       0  5026.0    0.05       0  5274.8   0.075       0
  5515.2    0.05       0  5718.5   0.075       0  5973.1    0.05       0
Bank Sta=4994.6,5026
Exp/Cntr=0.3,0.1

Type RM Length L Ch R = 1,50479,439,439,439
BEGIN DESCRIPTION:
Cedar Creek 50479.02
END DESCRIPTION:
XS GIS Cut Line= 3
      1588811.01      6843010.19      1590734.65      6842996.30
      1592734.62      6842656.03
#Sta/Elev= 30
  3094.7 1718.15  3291.2 1717.93  3531.9 1717.37  3778.7 1715.35  3914.0 1717.52
  4038.7 1720.32  4048.7 1716.63  4087.3 1713.04  4268.7 1713.31  4324.4 1710.90
  4378.7 1707.59  4388.7 1703.57  4398.7 1703.32  4428.7 1707.84  4468.7 1709.16
  4488.7 1706.28  4778.7 1705.90  4938.7 1701.47  4983.7 1695.33  4984.5 1694.33
  5015.1 1695.33  5059.3 1702.02  5573.1 1703.87  5901.2 1702.64  5911.4 1700.33
  5989.7 1699.46  6574.3 1708.21  6725.8 1713.38  6883.2 1718.49  7047.1 1717.38
#Mann=9,-1,0
  3094.7    0.05       0  3291.2   0.075       0  3531.9     0.1       0
  3914.0   0.075       0  4324.4    0.05       0  4983.7   0.035       0
  5015.1    0.05       0  6574.3    0.12       0  6725.8    0.05       0
Bank Sta=4983.7,5015.1
Exp/Cntr=0.3,0.1

Type RM Length L Ch R = 1,50040,502,502,502
BEGIN DESCRIPTION:
Cedar Creek 50040.4
END DESCRIPTION:
XS GIS Cut Line= 3
      1588831.86      6843433.80      1590838.81      6843392.14
      1593080.89      6843406.02
#Sta/Elev= 30
  2975.4 1718.00  3425.0 1715.23  3931.9 1713.78  3958.7 1711.03  4118.8 1712.85
  4388.8 1708.35  4408.8 1706.06  4538.6 1706.42  4611.8 1708.23  4718.9 1702.79
  4818.9 1704.24  4838.9 1702.22  4942.6 1702.77  4989.0 1697.66  4993.8 1694.31
  4994.6 1693.31  5025.2 1694.31  5079.0 1701.68  5359.0 1698.60  5469.0 1701.59
  5669.0 1701.46  5739.0 1700.02  5749.0 1698.15  5789.0 1699.50  5829.0 1697.83
  5849.0 1699.48  6009.0 1701.57  6559.0 1706.42  6999.0 1715.13  7224.9 1715.10
#Mann=7,-1,0
  2975.4    0.05       0  3425.0     0.1       0  3931.9    0.05       0
  4538.6   0.075       0  4611.8    0.05       0  4993.8   0.035       0
  5025.2    0.05       0
Bank Sta=4993.8,5025.2
Exp/Cntr=0.3,0.1

Type RM Length L Ch R = 1,49538,546,546,546
BEGIN DESCRIPTION:
Cedar Creek 49537.77
END DESCRIPTION:
XS GIS Cut Line= 3
      1588769.35      6843996.30      1590949.92      6843864.36
      1593199.90      6843628.25
#Sta/Elev= 30
  2810.2 1720.14  3021.5 1717.96  3045.1 1717.60  3120.8 1716.33  3627.3 1714.37
  3687.5 1711.71  3867.8 1709.75  4118.2 1710.69  4412.3 1705.65  4511.6 1704.97
  4759.4 1703.13  4839.6 1697.85  4949.8 1697.04  4979.3 1693.62  4979.9 1692.62
  5004.5 1693.62  5006.3 1696.26  5050.1 1700.73  5382.0 1699.08  5432.2 1701.06
  5502.6 1698.61  5653.4 1699.88  5683.6 1702.31  5713.8 1702.12  5743.9 1697.00
  5881.8 1701.80  6066.2 1702.48  6605.7 1710.89  6975.0 1714.62  7257.1 1714.71
#Mann=11,-1,0
  2810.2    0.05       0  3021.5   0.075       0  3045.1    0.05       0
  3120.8     0.1       0  4412.3   0.075       0  4511.6    0.05       0
  4979.3   0.035       0  5004.5    0.05       0  5881.8   0.075       0
  6605.7    0.05       0  6975.0     0.1       0
Bank Sta=4979.3,5004.5
Exp/Cntr=0.3,0.1

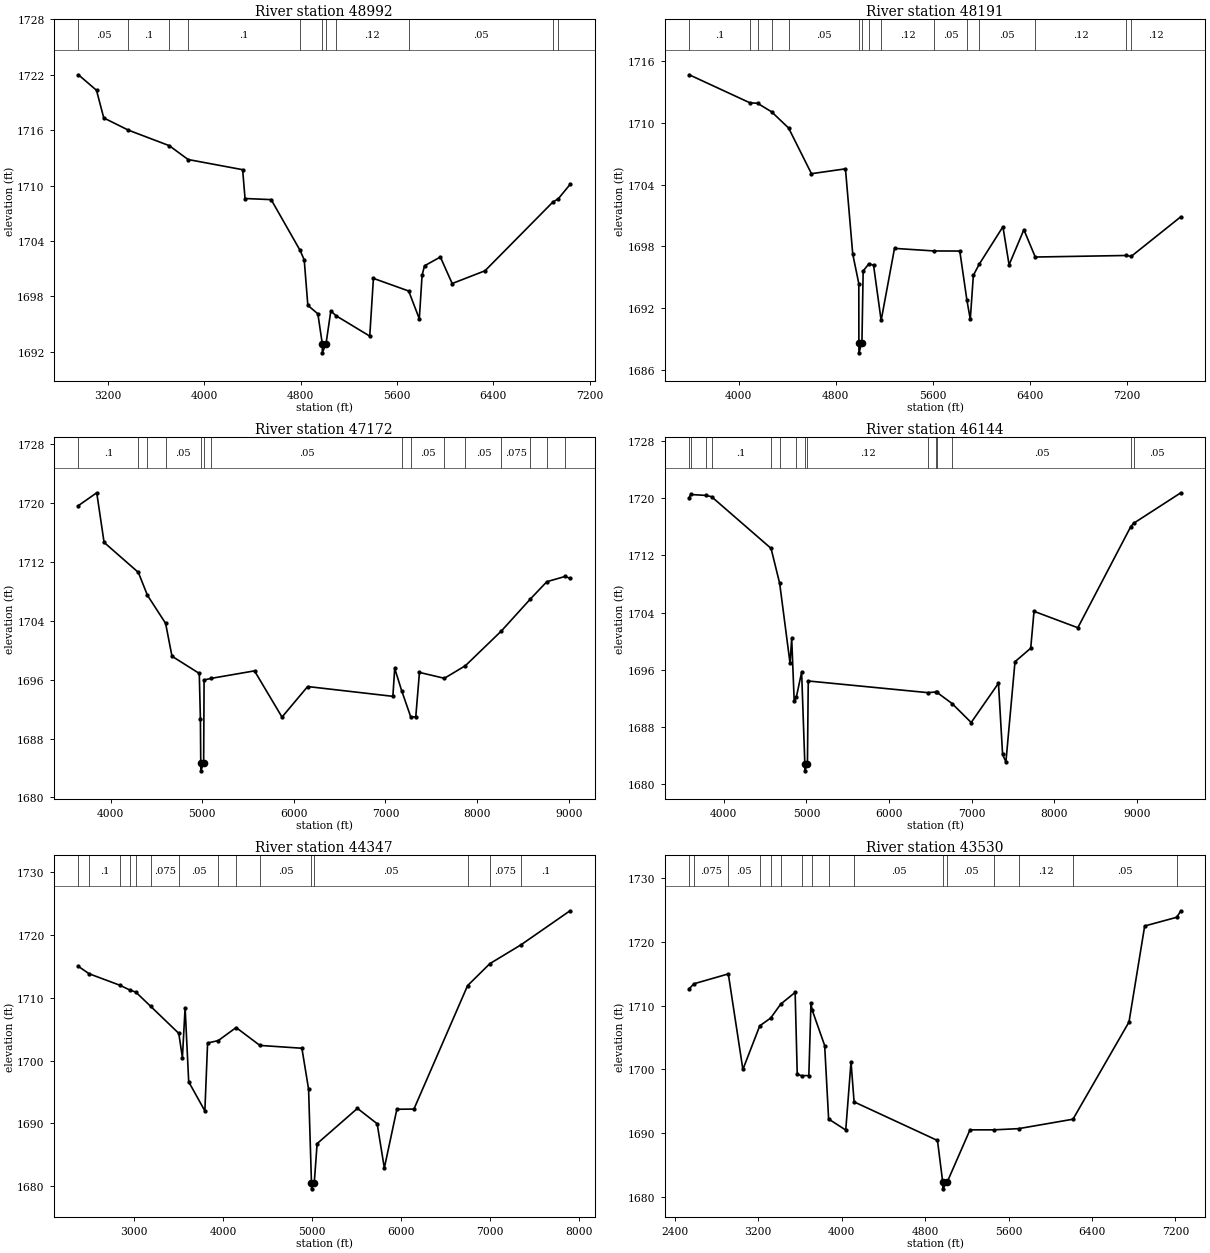
Type RM Length L Ch R = 1,48992,801,801,801
BEGIN DESCRIPTION:
Cedar Creek 48991.82
END DESCRIPTION:
XS GIS Cut Line= 3
      1588915.24      6844537.97      1590956.87      6844378.25
      1592970.39      6844079.69
#Sta/Elev= 30
  2953.9 1721.99  3104.1 1720.31  3164.3 1717.32  3368.6 1716.00  3708.2 1714.32
  3864.7 1712.82  4317.8 1711.72  4337.9 1708.60  4554.9 1708.48  4794.9 1702.99
  4829.4 1701.96  4859.5 1697.04  4942.8 1696.12  4979.2 1692.90  4980.0 1691.90
  5010.7 1692.90  5050.4 1696.43  5094.4 1695.91  5373.7 1693.71  5404.2 1699.96
  5697.3 1698.59  5785.4 1695.58  5808.6 1700.31  5828.8 1701.32  5960.3 1702.27
  6058.3 1699.40  6331.1 1700.78  6895.8 1708.23  6939.1 1708.56  7037.3 1710.12
#Mann=11,-1,0
  2953.9    0.05       0  3368.6     0.1       0  3708.2   0.075       0
  3864.7     0.1       0  4794.9    0.05       0  4979.2   0.035       0
  5010.7    0.05       0  5094.4    0.12       0  5697.3    0.05       0
  6895.8   0.075       0  6939.1    0.05       0
Bank Sta=4979.2,5010.7
Exp/Cntr=0.3,0.1

Type RM Length L Ch R = 1,48191,1019,1019,1019
BEGIN DESCRIPTION:
Cedar Creek 48190.5
END DESCRIPTION:
XS GIS Cut Line= 3
      1589748.57      6845079.64      1591165.20      6845065.75
      1593758.96      6844618.11
#Sta/Elev= 30
  3593.2 1714.66  4090.6 1711.95  4156.1 1711.89  4270.9 1711.07  4411.6 1709.49
  4599.7 1705.06  4879.7 1705.53  4939.7 1697.26  4989.7 1694.39  4990.3 1688.67
  4990.9 1687.67  5015.5 1688.67  5025.5 1695.61  5072.8 1696.32  5111.2 1696.18
  5173.7 1690.81  5283.7 1697.81  5608.8 1697.56  5821.5 1697.55  5880.3 1692.76
  5907.9 1690.92  5933.1 1695.19  5981.3 1696.27  6176.7 1699.91  6227.4 1696.21
  6349.2 1699.62  6443.0 1696.97  7192.6 1697.12  7233.1 1697.03  7642.0 1700.88
#Mann=15,-1,0
  3593.2     0.1       0  4090.6   0.075       0  4156.1     0.1       0
  4270.9   0.075       0  4411.6    0.05       0  4990.3   0.035       0
  5015.5    0.05       0  5072.8    0.05       0  5173.7    0.12       0
  5608.8    0.05       0  5880.3    0.12       0  5981.3    0.05       0
  6443.0    0.12       0  7192.6    0.05       0  7233.1    0.12       0
Bank Sta=4990.3,5015.5
Exp/Cntr=0.3,0.1

Type RM Length L Ch R = 1,47172,1028,1028,1028
BEGIN DESCRIPTION:
Cedar Creek 47171.72
END DESCRIPTION:
XS GIS Cut Line= 3
      1589755.49      6846051.86      1591352.70      6845968.53
      1595118.38      6845935.82
#Sta/Elev= 30
  3649.8 1719.64  3849.6 1721.38  3929.7 1714.64  4303.5 1710.57  4402.7 1707.46
  4601.3 1703.64  4670.7 1699.18  4968.7 1696.84  4981.1 1690.60  4984.8 1684.61
  4985.6 1683.61  5016.4 1684.61  5021.2 1695.95  5097.7 1696.17  5571.5 1697.19
  5871.5 1690.91  6151.5 1695.06  7081.6 1693.73  7101.6 1697.52  7177.5 1694.50
  7276.5 1690.94  7331.6 1690.94  7371.6 1696.98  7643.7 1696.18  7873.9 1697.90
  8266.8 1702.62  8581.5 1706.94  8761.9 1709.30  8959.9 1710.01  9015.0 1709.77
#Mann=15,-1,0
  3649.8     0.1       0  4303.5    0.05       0  4402.7   0.075       0
  4601.3    0.05       0  4984.8    0.07       0  5016.4    0.05       0
  5097.7    0.05       0  7177.5    0.12       0  7276.5    0.05       0
  7643.7   0.075       0  7873.9    0.05       0  8266.8   0.075       0
  8581.5     0.1       0  8761.9   0.075       0  8959.9    0.05       0
Bank Sta=4984.8,5016.4
Exp/Cntr=0.3,0.1

Type RM Length L Ch R = 1,46144,1797,1797,1797
BEGIN DESCRIPTION:
Cedar Creek 46144.26
END DESCRIPTION:
XS GIS Cut Line= 3
      1589387.43      6846947.69      1591366.59      6846836.58
      1595330.94      6846753.55
#Sta/Elev= 30
  3581.6 1720.11  3598.3 1720.54  3784.6 1720.41  3851.5 1720.23  4571.3 1712.99
  4675.7 1708.08  4801.1 1696.89  4821.1 1700.39  4851.2 1691.62  4877.5 1692.16
  4941.3 1695.65  4979.9 1682.82  4980.7 1681.82  5011.5 1682.82  5021.4 1694.41
  6464.3 1692.78  6563.4 1692.86  6576.5 1692.83  6761.5 1691.25  6992.6 1688.59
  7322.7 1694.09  7372.7 1684.12  7412.7 1683.06  7522.7 1697.11  7712.8 1699.00
  7752.8 1704.17  8282.9 1701.87  8923.9 1716.05  8957.3 1716.50  9529.1 1720.78
#Mann=15,-1,0
  3581.6   0.075       0  3598.3     0.1       0  3784.6   0.075       0
  3851.5     0.1       0  4571.3   0.075       0  4675.7    0.05       0
  4877.5    0.12       0  4979.9   0.035       0  5011.5    0.12       0
  6464.3   0.075       0  6563.4    0.05       0  6576.5   0.075       0
  6761.5    0.05       0  8923.9   0.075       0  8957.3    0.05       0
Bank Sta=4979.9,5011.5
Exp/Cntr=0.3,0.1

Type RM Length L Ch R = 1,44347,817,817,817
BEGIN DESCRIPTION:
Cedar Creek 44755.14
END DESCRIPTION:
XS GIS Cut Line= 3
      1589498.58      6847940.74      1591679.09      6847635.19
      1594977.73      6847269.15
#Sta/Elev= 30
  2374.9 1715.02  2494.3 1713.85  2841.1 1712.01  2954.3 1711.24  3019.3 1710.92
  3187.9 1708.63  3502.0 1704.34  3542.6 1700.48  3572.9 1708.44  3613.3 1696.61
  3794.9 1691.98  3825.4 1702.80  3945.0 1703.19  4145.8 1705.27  4412.7 1702.42
  4884.5 1701.97  4959.6 1695.44  4991.9 1680.55  4992.6 1679.55  5023.5 1680.55
  5055.5 1686.76  5508.3 1692.38  5729.7 1689.93  5810.2 1682.87  5951.0 1692.24
  6142.6 1692.27  6745.4 1711.96  6995.4 1715.46  7344.9 1718.46  7895.6 1723.89
#Mann=15,-1,0
  2374.9   0.075       0  2494.3     0.1       0  2841.1    0.05       0
  2954.3   0.075       0  3019.3    0.05       0  3187.9   0.075       0
  3502.0    0.05       0  3945.0   0.075       0  4145.8     0.1       0
  4412.7    0.05       0  4991.9    0.05       0  5023.5    0.05       0
  6745.4     0.1       0  6995.4   0.075       0  7344.9     0.1       0
Bank Sta=4991.9,5023.5
Exp/Cntr=0.3,0.1

Type RM Length L Ch R = 1,43530,594,594,594
BEGIN DESCRIPTION:
Cedar Creek 43529.68
END DESCRIPTION:
XS GIS Cut Line= 3
      1589470.80      6848649.07      1591929.09      6848281.03
      1594150.63      6848107.47
#Sta/Elev= 30
  2538.4 1712.67  2583.5 1713.44  2913.0 1714.99  3052.7 1699.99  3214.5 1706.84
  3319.2 1708.06  3415.6 1710.25  3553.8 1712.09  3574.0 1699.21  3616.6 1699.01
  3685.2 1699.04  3705.5 1710.35  3717.1 1709.32  3836.9 1703.75  3874.9 1692.21
  4039.1 1690.48  4089.7 1701.17  4119.2 1694.90  4918.8 1688.84  4969.4 1682.25
  4970.1 1681.25  5010.2 1682.25  5230.6 1690.51  5460.8 1690.51  5696.9 1690.70
  6218.1 1692.18  6755.3 1707.44  6905.7 1722.51  7213.2 1723.88  7252.4 1724.90
#Mann=16,-1,0
  2538.4    0.05       0  2583.5   0.075       0  2913.0    0.05       0
  3214.5   0.075       0  3319.2    0.05       0  3415.6     0.1       0
  3616.6   0.075       0  3717.1    0.05       0  3874.9   0.075       0
  4119.2    0.05       0  4969.4    0.07       0  5010.2    0.05       0
  5460.8    0.05       0  5696.9    0.12       0  6218.1    0.05       0
  7213.2   0.075       0
Bank Sta=4969.4,5010.2
Exp/Cntr=0.3,0.1