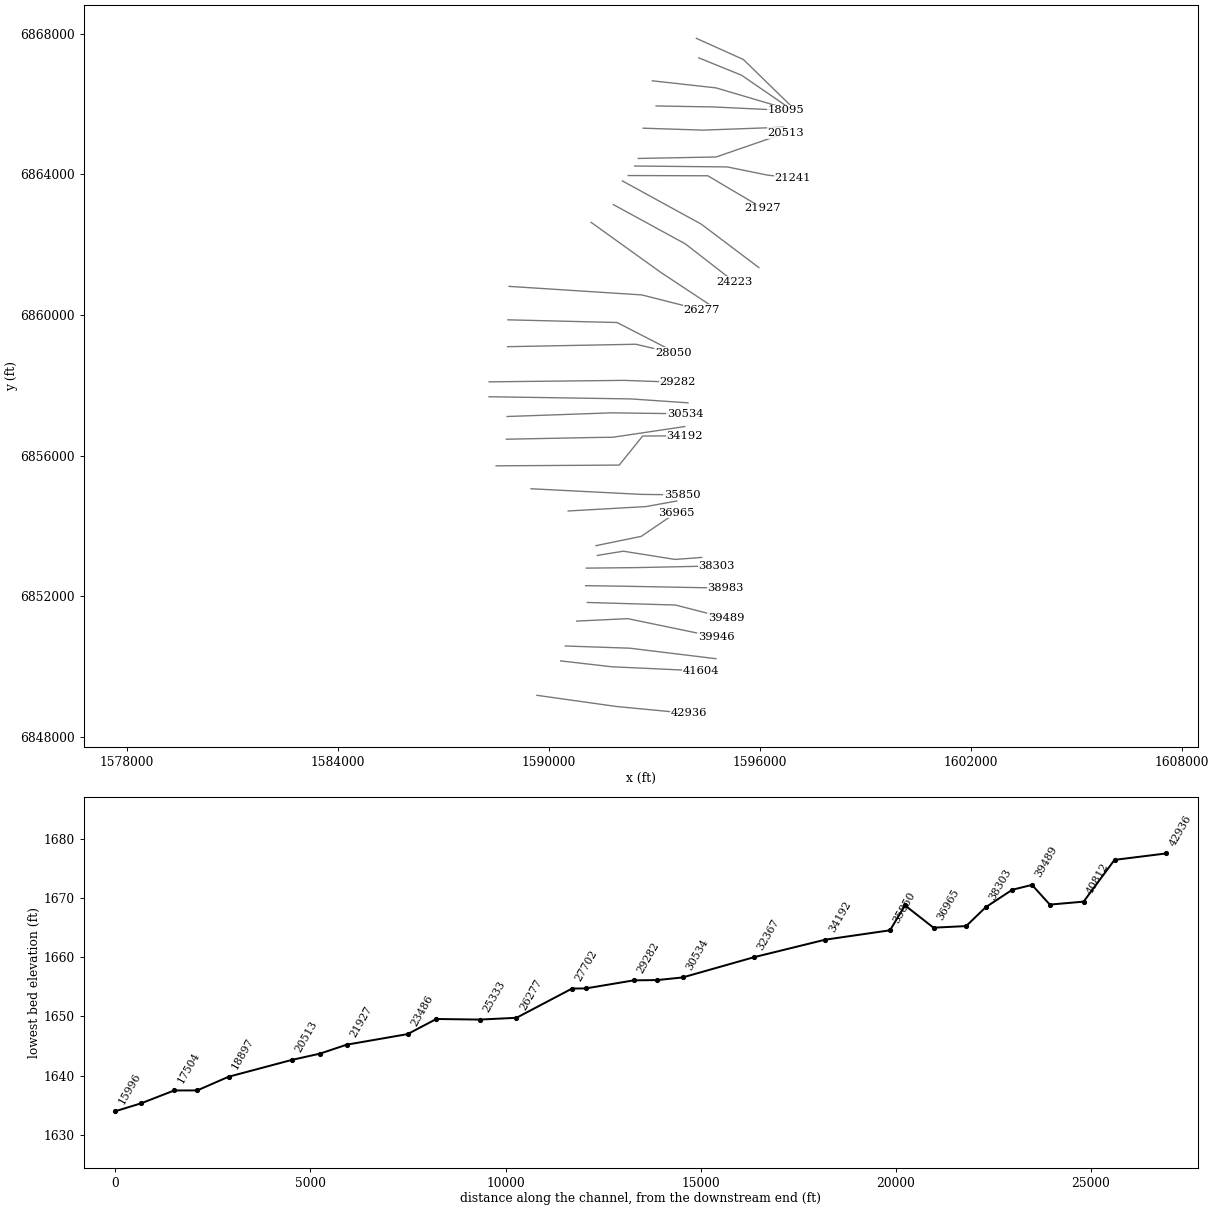
HEC-RAS study Cedar Creek.prj: Cedar Creek Base Level Engineering

--- Cedar Creek.g01 (geometry) --- (continued)

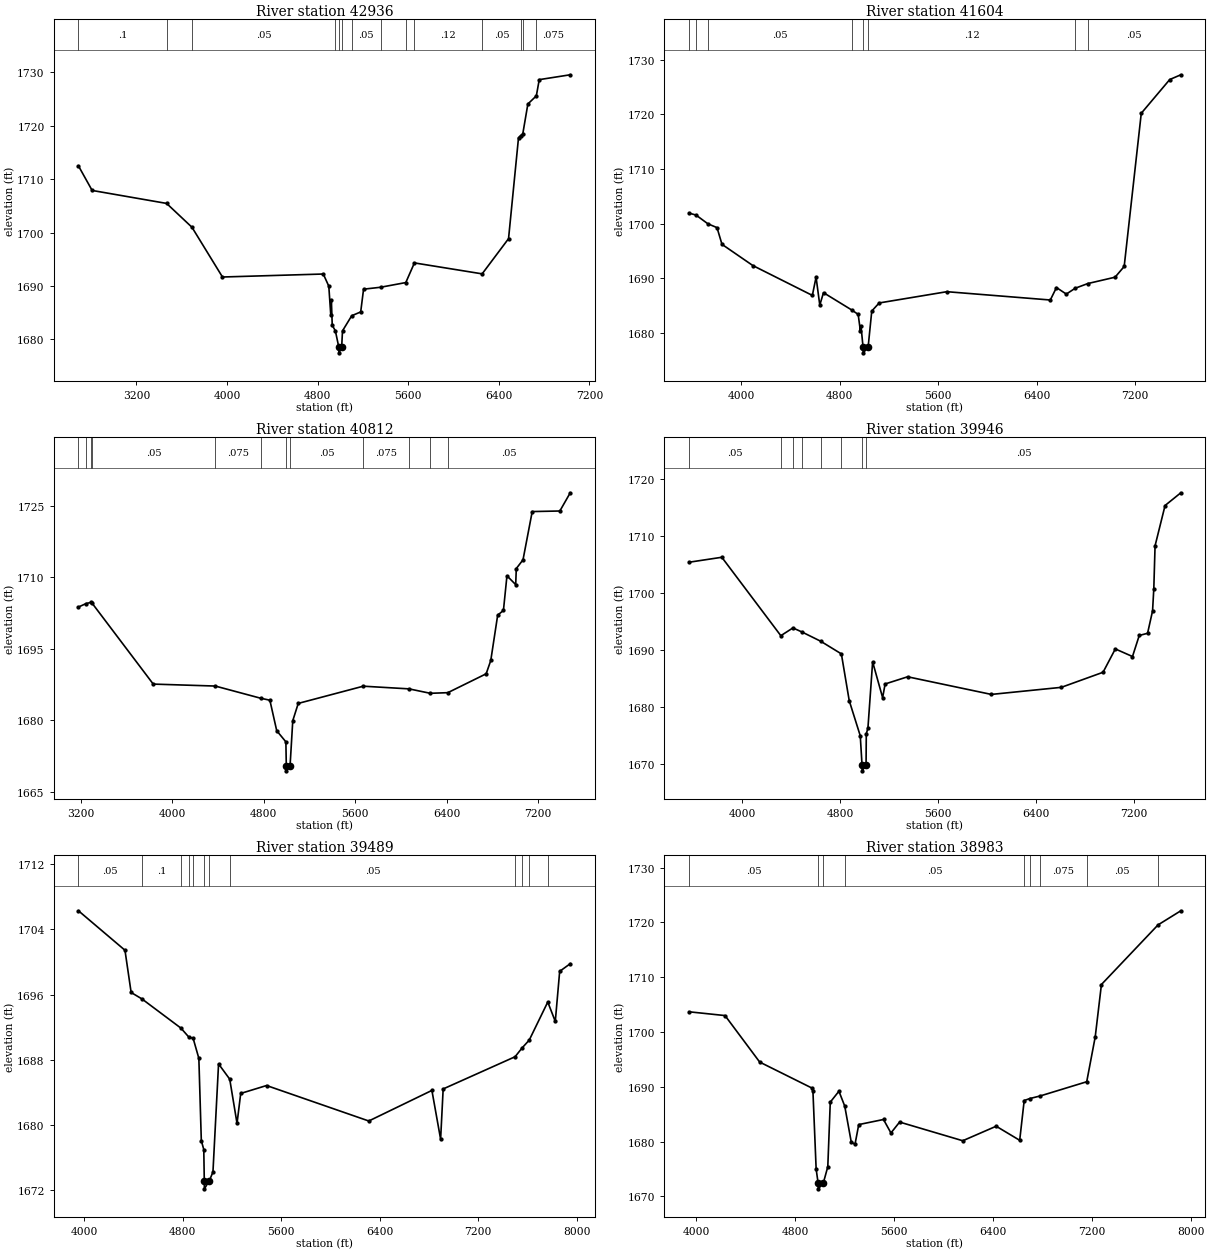
Type RM Length L Ch R = 1,42936,1332,1332,1332
BEGIN DESCRIPTION:
Cedar Creek 42936.21
END DESCRIPTION:
XS GIS Cut Line= 3
      1589665.17      6849183.81      1591936.03      6848864.36
      1593977.67      6848669.92
#Sta/Elev= 30
  2687.3 1712.50  2808.3 1707.90  3466.1 1705.47  3690.2 1701.00  3959.5 1691.69
  4850.0 1692.25  4898.7 1689.97  4916.2 1684.56  4921.2 1687.43  4929.0 1682.65
  4956.7 1681.61  4987.6 1678.49  4988.1 1677.49  5012.2 1678.49  5019.7 1681.61
  5101.1 1684.44  5180.4 1685.15  5205.7 1689.41  5355.7 1689.77  5578.7 1690.65
  5654.9 1694.33  6253.1 1692.28  6486.3 1698.87  6574.3 1717.77  6593.0 1718.16
  6612.1 1718.50  6657.0 1724.09  6731.8 1725.61  6757.5 1728.65  7031.4 1729.56
#Mann=14,-1,0
  2687.3     0.1       0  3466.1   0.075       0  3690.2    0.05       0
  4956.7    0.12       0  4987.6    0.07       0  5012.2    0.12       0
  5101.1    0.05       0  5355.7   0.075       0  5578.7    0.05       0
  5654.9    0.12       0  6253.1    0.05       0  6593.0   0.075       0
  6612.1    0.05       0  6731.8   0.075       0
Bank Sta=4987.6,5012.2
Exp/Cntr=0.3,0.1

Type RM Length L Ch R = 1,41604,792,792,792
BEGIN DESCRIPTION:
Cedar Creek 41604.25
END DESCRIPTION:
XS GIS Cut Line= 3
      1590338.79      6850162.97      1591783.26      6849996.30
      1594324.96      6849878.25
#Sta/Elev= 30
  3574.7 1701.95  3631.7 1701.59  3727.7 1700.00  3802.4 1699.29  3842.7 1696.24
  4093.6 1692.36  4577.5 1686.90  4607.7 1690.24  4637.9 1685.13  4668.1 1687.40
  4897.2 1684.24  4950.0 1683.43  4967.7 1680.45  4972.7 1681.37  4989.8 1677.40
  4990.5 1676.40  5030.7 1677.40  5060.5 1684.04  5120.6 1685.52  5671.2 1687.58
  6512.1 1686.06  6562.1 1688.34  6642.2 1687.14  6714.3 1688.21  6817.4 1689.07
  7038.7 1690.23  7112.7 1692.19  7251.6 1720.20  7483.1 1726.37  7573.2 1727.24
#Mann=8,-1,0
  3574.7     0.1       0  3631.7   0.075       0  3727.7    0.05       0
  4897.2    0.12       0  4989.8    0.07       0  5030.7    0.12       0
  6714.3    0.12       0  6817.4    0.05       0
Bank Sta=4989.8,5030.7
Exp/Cntr=0.3,0.1

Type RM Length L Ch R = 1,40812,866,866,866
BEGIN DESCRIPTION:
Cedar Creek 40811.84
END DESCRIPTION:
XS GIS Cut Line= 3
      1590470.77      6850586.58      1592304.09      6850524.08
      1594755.48      6850225.47
#Sta/Elev= 30
  3178.9 1703.71  3247.0 1704.45  3286.4 1704.67  3296.7 1704.57  3833.5 1687.55
  4376.4 1687.14  4773.0 1684.59  4854.1 1684.17  4914.1 1677.77  4994.2 1675.44
  4997.9 1670.36  4998.5 1669.36  5030.7 1670.36  5054.5 1679.88  5102.4 1683.50
  5671.4 1687.11  6071.6 1686.55  6257.8 1685.62  6411.3 1685.75  6746.9 1689.71
  6787.2 1692.50  6847.7 1702.01  6898.0 1703.00  6928.8 1710.26  7005.4 1708.41
  7010.5 1711.78  7069.3 1713.61  7149.9 1723.73  7391.7 1723.85  7482.8 1727.67
#Mann=12,-1,0
  3178.9   0.075       0  3247.0    0.05       0  3286.4   0.075       0
  3296.7    0.05       0  4376.4   0.075       0  4773.0    0.05       0
  4997.9   0.035       0  5030.7    0.05       0  5671.4   0.075       0
  6071.6    0.05       0  6257.8    0.12       0  6411.3    0.05       0
Bank Sta=4997.9,5030.7
Exp/Cntr=0.3,0.1

Type RM Length L Ch R = 1,39946,457,457,457
BEGIN DESCRIPTION:
Cedar Creek 39945.95
END DESCRIPTION:
XS GIS Cut Line= 3
      1590797.19      6851294.92      1592248.53      6851364.36
      1594761.17      6850843.79
#Sta/Elev= 30
  3565.7 1705.41  3833.8 1706.28  4316.0 1692.54  4414.9 1693.90  4490.5 1693.17
  4641.7 1691.57  4810.8 1689.35  4875.0 1681.15  4965.1 1675.00  4979.7 1669.86
  4980.3 1668.86  5012.5 1669.86  5014.4 1675.32  5027.9 1676.39  5066.2 1687.95
  5147.9 1681.68  5168.2 1684.08  5352.1 1685.34  6036.3 1682.25  6608.2 1683.49
  6949.1 1686.13  7049.4 1690.22  7189.7 1688.89  7245.0 1692.58  7312.9 1692.96
  7353.7 1696.88  7363.9 1700.77  7374.2 1708.29  7455.9 1715.35  7584.7 1717.58
#Mann=8,-1,0
  3565.7    0.05       0  4316.0     0.1       0  4414.9   0.075       0
  4490.5     0.1       0  4641.7   0.075       0  4810.8    0.05       0
  4979.7    0.05       0  5012.5    0.05       0
Bank Sta=4979.7,5012.5
Exp/Cntr=0.3,0.1

Type RM Length L Ch R = 1,39489,506,506,506
BEGIN DESCRIPTION:
Mapping XS 6a402758
END DESCRIPTION:
XS GIS Cut Line= 3
      1591097.12      6851824.71      1593607.58      6851751.79
      1595045.06      6851382.01
#Sta/Elev= 30
  3952.5 1706.28  4330.5 1701.44  4380.6 1696.26  4468.4 1695.47  4785.2 1691.89
  4848.8 1690.80  4884.3 1690.64  4930.8 1688.18  4950.8 1678.09  4970.8 1677.00
  4974.9 1673.18  4975.7 1672.18  5016.0 1673.18  5045.3 1674.24  5090.9 1687.50
  5181.6 1685.63  5240.9 1680.21  5270.9 1683.88  5481.0 1684.85  6311.4 1680.50
  6824.2 1684.25  6895.0 1678.27  6915.7 1684.43  7500.0 1688.38  7557.0 1689.46
  7615.0 1690.42  7765.6 1695.09  7826.7 1692.71  7862.3 1698.85  7948.3 1699.79
#Mann=12,-1,0
  3952.5    0.05       0  4468.4     0.1       0  4785.2   0.075       0
  4848.8     0.1       0  4884.3    0.05       0  4974.9    0.07       0
  5016.0    0.05       0  5181.6    0.05       0  7500.0   0.075       0
  7557.0    0.05       0  7615.0   0.075       0  7765.6    0.05       0
Bank Sta=4974.9,5016
Exp/Cntr=0.3,0.1

Type RM Length L Ch R = 1,38983,680,680,680
BEGIN DESCRIPTION:
Cedar Creek 38982.72
END DESCRIPTION:
XS GIS Cut Line= 3
      1591054.05      6852301.86      1592081.87      6852287.97
      1595026.33      6852232.41
#Sta/Elev= 30
  3943.7 1703.68  4234.7 1702.99  4514.7 1694.50  4934.7 1689.78  4944.7 1689.20
  4970.7 1674.97  4986.9 1672.36  4987.6 1671.36  5027.9 1672.36  5064.8 1675.40
  5084.8 1687.19  5154.8 1689.18  5201.7 1686.46  5254.8 1679.84  5284.8 1679.51
  5314.8 1683.09  5514.8 1684.02  5574.9 1681.56  5644.9 1683.55  6155.0 1680.14
  6425.0 1682.79  6615.0 1680.22  6651.3 1687.48  6696.2 1687.84  6781.3 1688.32
  7156.4 1690.91  7225.1 1699.10  7275.2 1708.66  7732.4 1719.54  7916.6 1722.12
#Mann=9,-1,0
  3943.7    0.05       0  4986.9   0.035       0  5027.9    0.05       0
  5201.7    0.05       0  6651.3   0.075       0  6696.2    0.05       0
  6781.3   0.075       0  7156.4    0.05       0  7732.4   0.075       0
Bank Sta=4986.9,5027.9
Exp/Cntr=0.3,0.1

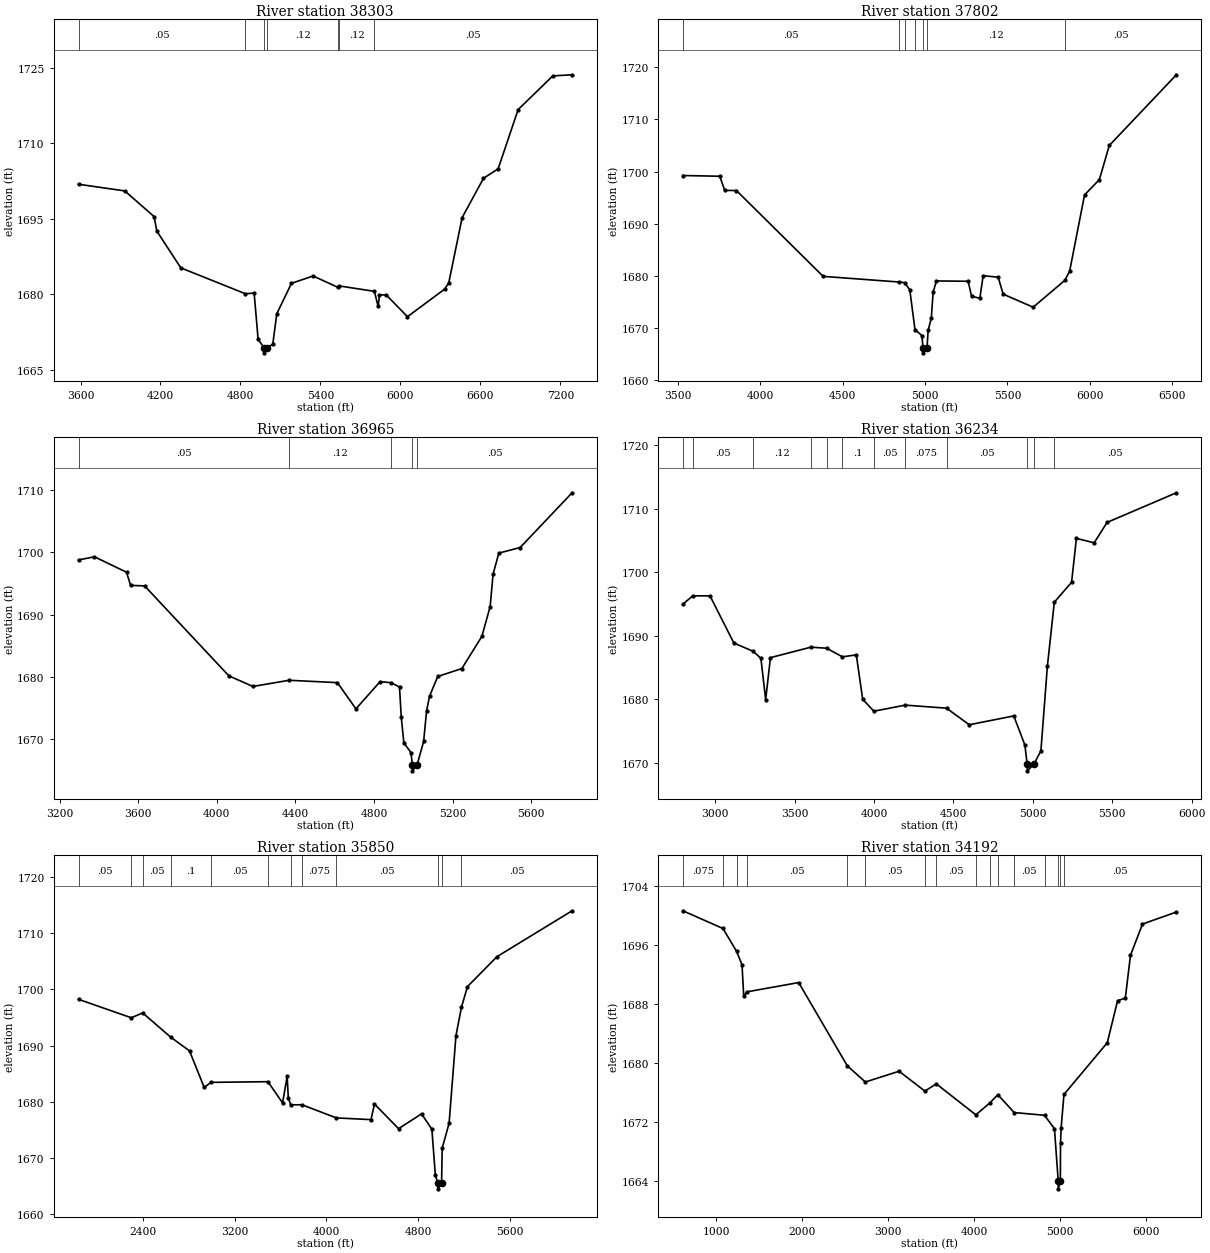
Type RM Length L Ch R = 1,38303,501,501,501
BEGIN DESCRIPTION:
Cedar Creek 38302.63
END DESCRIPTION:
XS GIS Cut Line= 3
      1591067.95      6852801.86      1592484.65      6852815.75
      1594769.36      6852864.36
#Sta/Elev= 30
  3585.2 1701.85  3932.3 1700.53  4152.3 1695.43  4172.3 1692.57  4352.3 1685.27
  4837.5 1680.13  4902.3 1680.29  4932.3 1671.10  4976.4 1669.42  4976.8 1668.42
  5001.0 1669.42  5042.3 1670.15  5072.3 1676.17  5182.4 1682.21  5345.1 1683.66
  5528.6 1681.43  5540.0 1681.69  5804.0 1680.62  5832.5 1677.62  5842.5 1679.91
  5892.5 1679.91  6052.6 1675.59  6332.6 1681.08  6362.6 1682.36  6462.6 1695.24
  6622.7 1703.03  6732.7 1704.92  6882.7 1716.67  7142.8 1723.34  7287.2 1723.56
#Mann=7,-1,0
  3585.2    0.05       0  4837.5    0.12       0  4976.4    0.07       0
  5001.0    0.12       0  5528.6    0.05       0  5540.0    0.12       0
  5804.0    0.05       0
Bank Sta=4976.4,5001
Exp/Cntr=0.3,0.1

Type RM Length L Ch R = 1,37802,837,837,837
BEGIN DESCRIPTION:
Mapping XS 95f4fe48
END DESCRIPTION:
XS GIS Cut Line= 4
      1591383.64      6853163.26      1592123.20      6853283.04
      1593597.16      6853048.67      1594351.21      6853105.87
#Sta/Elev= 30
  3528.4 1699.23  3752.6 1699.09  3783.0 1696.38  3854.0 1696.35  4380.7 1679.90
  4843.9 1678.81  4876.1 1678.69  4907.2 1677.29  4938.6 1669.70  4980.8 1668.54
  4987.2 1666.24  4987.6 1665.24  5011.8 1666.24  5018.6 1669.55  5037.9 1671.93
  5049.0 1676.94  5069.2 1679.02  5261.6 1678.96  5281.9 1676.12  5332.5 1675.69
  5352.7 1680.03  5443.9 1679.74  5474.2 1676.49  5656.5 1673.99  5849.5 1679.15
  5878.2 1680.92  5968.5 1695.50  6058.7 1698.46  6118.9 1704.99  6526.3 1718.54
#Mann=7,-1,0
  3528.4    0.05       0  4843.9    0.12       0  4876.1    0.05       0
  4938.6    0.12       0  4987.2    0.07       0  5011.8    0.12       0
  5849.5    0.05       0
Bank Sta=4987.2,5011.8
Exp/Cntr=0.3,0.1

Type RM Length L Ch R = 1,36965,731,731,731
BEGIN DESCRIPTION:
Cedar Creek 36964.96
END DESCRIPTION:
XS GIS Cut Line= 3
      1591345.72      6853440.74      1592630.48      6853704.64
      1593623.49      6854378.22
#Sta/Elev= 30
  3296.3 1698.78  3377.2 1699.29  3540.6 1696.81  3561.1 1694.71  3632.5 1694.62
  4061.2 1680.20  4183.7 1678.50  4368.2 1679.49  4613.6 1679.11  4707.9 1674.91
  4830.7 1679.27  4887.4 1679.10  4929.6 1678.40  4938.5 1673.59  4951.7 1669.47
  4987.9 1667.90  4994.9 1665.97  4995.4 1664.97  5019.6 1665.97  5052.4 1669.69
  5067.3 1674.56  5082.3 1676.94  5124.2 1680.10  5247.0 1681.37  5348.8 1686.53
  5390.8 1691.30  5405.7 1696.50  5435.0 1699.88  5543.4 1700.77  5807.8 1709.55
#Mann=5,-1,0
  3296.3    0.05       0  4368.2    0.12       0  4887.4    0.05       0
  4994.9   0.035       0  5019.6    0.05       0
Bank Sta=4994.9,5019.6
Exp/Cntr=0.3,0.1

Type RM Length L Ch R = 1,36234,384,384,384
BEGIN DESCRIPTION:
Cedar Creek 36233.95
END DESCRIPTION:
XS GIS Cut Line= 3
      1590554.08      6854426.86      1592762.42      6854551.86
      1593644.40      6854711.59
#Sta/Elev= 30
  2795.6 1694.95  2858.9 1696.27  2966.8 1696.26  3117.0 1688.84  3237.6 1687.55
  3287.3 1686.44  3317.4 1679.94  3347.4 1686.54  3602.5 1688.19  3701.5 1688.02
  3800.5 1686.67  3888.3 1686.97  3928.3 1680.00  3998.5 1678.11  4196.5 1679.07
  4456.6 1678.59  4599.4 1675.98  4879.8 1677.37  4950.0 1672.77  4964.4 1669.73
  4965.2 1668.73  5005.6 1669.73  5050.7 1671.88  5091.4 1685.17  5135.1 1695.26
  5243.8 1698.40  5274.3 1705.30  5386.1 1704.61  5467.6 1707.82  5903.8 1712.48
#Mann=12,-1,0
  2795.6   0.075       0  2858.9    0.05       0  3237.6    0.12       0
  3602.5    0.05       0  3701.5   0.075       0  3800.5     0.1       0
  3998.5    0.05       0  4196.5   0.075       0  4456.6    0.05       0
  4964.4    0.07       0  5005.6    0.05       0  5135.1    0.05       0
Bank Sta=4964.4,5005.6
Exp/Cntr=0.3,0.1

Type RM Length L Ch R = 1,35850,1658,1658,1658
BEGIN DESCRIPTION:
Cedar Creek 35849.92
END DESCRIPTION:
XS GIS Cut Line= 3
      1589498.53      6855058.80      1592637.42      6854899.08
      1593797.19      6854885.19
#Sta/Elev= 30
  1839.6 1698.24  2299.6 1694.96  2398.9 1695.82  2645.2 1691.47  2807.3 1689.07
  2935.1 1682.56  2994.5 1683.47  3490.9 1683.59  3618.4 1679.81  3658.4 1684.52
  3668.4 1680.69  3689.4 1679.48  3788.7 1679.48  4086.5 1677.15  4389.4 1676.84
  4419.4 1679.62  4629.7 1675.23  4829.9 1677.87  4920.0 1675.13  4950.1 1667.01
  4971.6 1665.53  4972.2 1664.53  5004.5 1665.53  5010.1 1671.77  5070.1 1676.19
  5130.1 1691.80  5177.9 1696.82  5230.1 1700.50  5487.8 1705.83  6142.4 1713.99
#Mann=12,-1,0
  1839.6    0.05       0  2299.6   0.075       0  2398.9    0.05       0
  2645.2     0.1       0  2994.5    0.05       0  3490.9    0.12       0
  3689.4    0.05       0  3788.7   0.075       0  4086.5    0.05       0
  4971.6    0.07       0  5004.5    0.05       0  5177.9    0.05       0
Bank Sta=4971.6,5004.5
Exp/Cntr=0.3,0.1

Type RM Length L Ch R = 1,34192,1825,1825,1825
BEGIN DESCRIPTION:
Cedar Creek 34191.86
END DESCRIPTION:
XS GIS Cut Line= 4
      1588505.45      6855711.58      1592005.48      6855732.41
      1592672.15      6856558.80      1593859.66      6856565.75
#Sta/Elev= 30
   607.9 1700.64  1075.4 1698.24  1234.7 1695.13  1297.5 1693.33  1317.5 1689.05
  1354.3 1689.65  1957.5 1690.91  2523.7 1679.63  2734.2 1677.43  3127.5 1678.89
  3427.1 1676.20  3561.0 1677.18  4021.0 1672.98  4186.9 1674.62  4277.6 1675.71
  4468.2 1673.29  4821.2 1672.92  4937.2 1671.10  4981.3 1663.95  4981.7 1662.95
  5006.0 1663.95  5007.6 1669.11  5014.6 1671.17  5047.9 1675.74  5552.6 1682.76
  5672.6 1688.46  5762.6 1688.80  5822.6 1694.60  5962.6 1698.84  6357.3 1700.47
#Mann=16,-1,0
   607.9   0.075       0  1075.4     0.1       0  1234.7   0.075       0
  1354.3    0.05       0  2523.7     0.1       0  2734.2    0.05       0
  3427.1    0.12       0  3561.0    0.05       0  4021.0    0.12       0
  4186.9    0.05       0  4277.6    0.12       0  4468.2    0.05       0
  4821.2    0.12       0  4981.3    0.07       0  5006.0    0.12       0
  5047.9    0.05       0
Bank Sta=4981.3,5006
Exp/Cntr=0.3,0.1

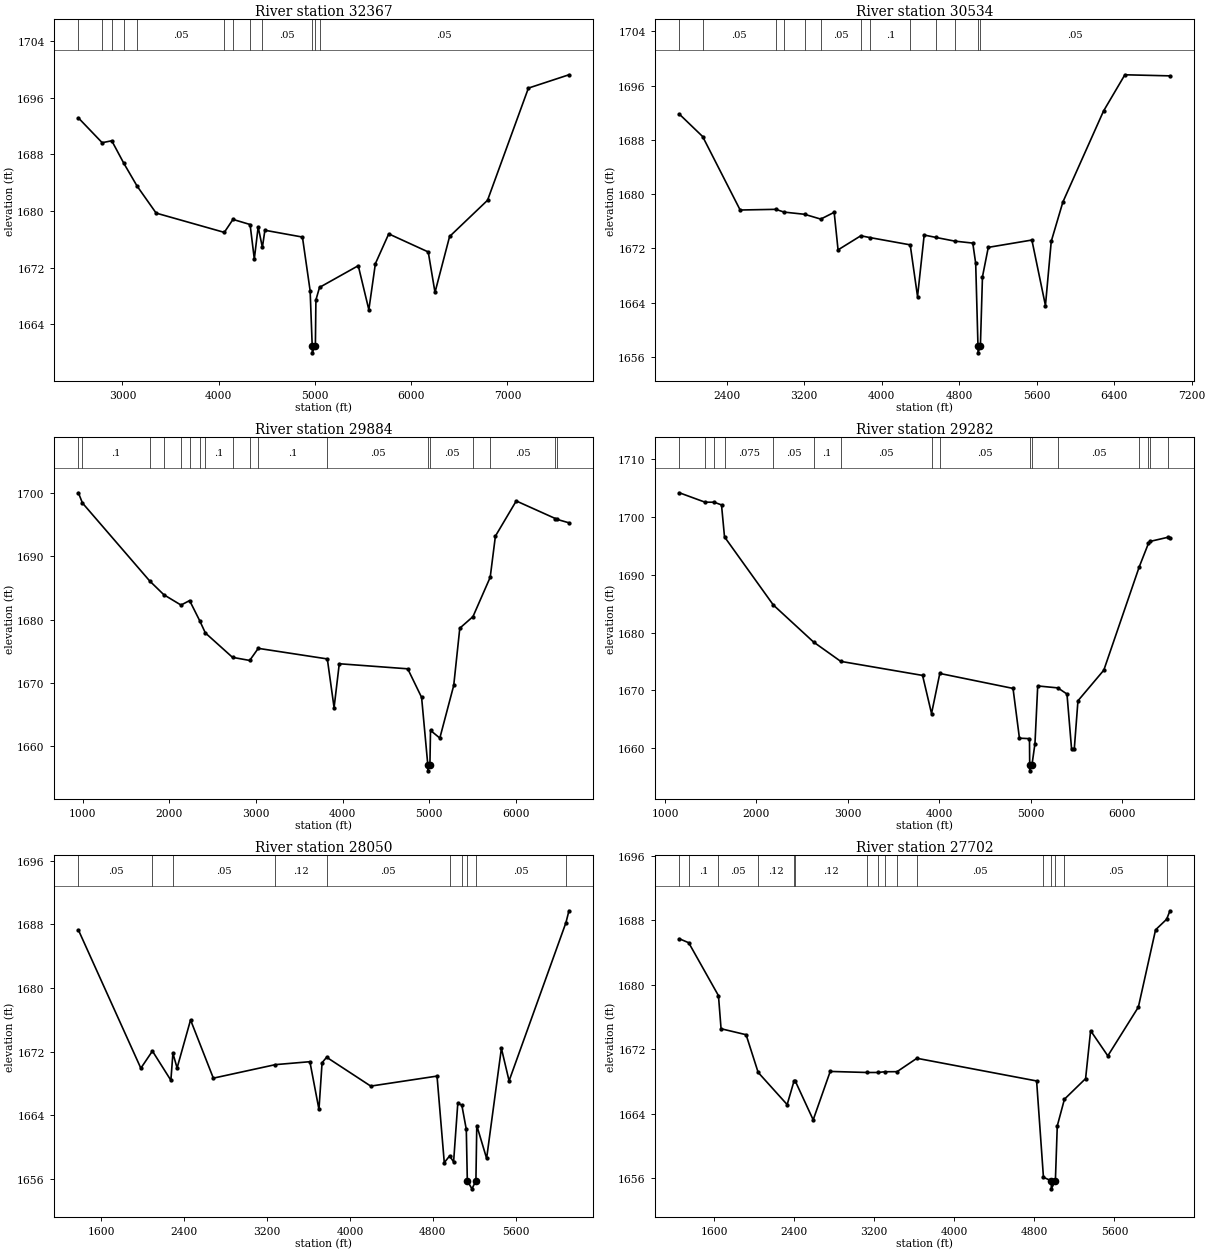
Type RM Length L Ch R = 1,32367,1833,1833,1833
BEGIN DESCRIPTION:
Cedar Creek 32366.81
END DESCRIPTION:
XS GIS Cut Line= 4
      1588797.12      6856468.53      1591283.26      6856517.14
      1591824.92      6856524.08      1593871.76      6856829.37
#Sta/Elev= 30
  2541.8 1693.14  2788.8 1689.64  2888.8 1689.91  3014.1 1686.73  3151.9 1683.52
  3349.8 1679.71  4058.0 1676.99  4148.3 1678.82  4326.1 1678.10  4370.0 1673.24
  4410.0 1677.76  4453.9 1674.88  4480.0 1677.29  4870.1 1676.33  4950.1 1668.75
  4971.6 1661.00  4972.2 1660.00  5004.6 1661.00  5010.1 1667.46  5047.6 1669.23
  5450.2 1672.29  5560.2 1666.08  5628.2 1672.58  5766.8 1676.78  6177.4 1674.23
  6247.6 1668.53  6399.3 1676.41  6793.6 1681.52  7218.2 1697.34  7639.6 1699.22
#Mann=12,-1,0
  2541.8     0.1       0  2788.8   0.075       0  2888.8    0.05       0
  3014.1   0.075       0  3151.9    0.05       0  4058.0   0.075       0
  4148.3     0.1       0  4326.1   0.075       0  4453.9    0.05       0
  4971.6    0.07       0  5004.6    0.05       0  5047.6    0.05       0
Bank Sta=4971.6,5004.6
Exp/Cntr=0.3,0.1

Type RM Length L Ch R = 1,30534,650,650,650
BEGIN DESCRIPTION:
Cedar Creek 30533.88
END DESCRIPTION:
XS GIS Cut Line= 3
      1588818.02      6857114.36      1591790.20      6857218.53
      1593880.21      6857190.75
#Sta/Elev= 30
  1911.0 1691.79  2151.1 1688.49  2538.4 1677.65  2906.1 1677.75  2992.4 1677.34
  3203.0 1677.02  3370.2 1676.31  3509.0 1677.31  3549.0 1671.77  3784.1 1673.85
  3883.1 1673.57  4293.9 1672.51  4369.5 1664.89  4438.1 1673.96  4557.6 1673.61
  4753.8 1673.06  4939.8 1672.77  4969.8 1669.79  4993.5 1657.58  4994.0 1656.58
  5018.4 1657.58  5039.8 1667.80  5099.8 1672.14  5549.9 1673.22  5689.9 1663.56
  5749.9 1673.03  5869.9 1678.83  6289.9 1692.26  6509.9 1697.60  6975.2 1697.44
#Mann=13,-1,0
  1911.0     0.1       0  2151.1    0.05       0  2906.1   0.075       0
  2992.4    0.05       0  3203.0   0.075       0  3370.2    0.05       0
  3784.1   0.075       0  3883.1     0.1       0  4293.9    0.05       0
  4557.6   0.075       0  4753.8    0.05       0  4993.5   0.035       0
  5018.4    0.05       0
Bank Sta=4993.5,5018.4
Exp/Cntr=0.3,0.1

Type RM Length L Ch R = 1,29884,602,602,602
BEGIN DESCRIPTION:
Cedar Creek 29883.9
END DESCRIPTION:
XS GIS Cut Line= 3
      1588304.11      6857676.86      1592345.76      6857614.36
      1593961.92      6857503.38
#Sta/Elev= 30
   949.2 1700.02   995.9 1698.41  1772.5 1686.10  1935.7 1683.93  2133.8 1682.30
  2232.9 1683.01  2349.2 1679.84  2414.8 1677.90  2728.1 1674.05  2926.3 1673.56
  3025.3 1675.47  3822.5 1673.80  3900.4 1666.12  3960.5 1673.04  4750.5 1672.24
  4910.6 1667.73  4981.8 1657.14  4982.2 1656.14  5006.6 1657.14  5013.4 1662.52
  5120.9 1661.31  5281.3 1669.61  5351.4 1678.65  5503.6 1680.48  5702.4 1686.69
  5762.4 1693.18  6003.0 1698.73  6455.2 1695.95  6467.9 1695.85  6611.3 1695.28
#Mann=18,-1,0
   949.2   0.075       0   995.9     0.1       0  1772.5   0.075       0
  1935.7     0.1       0  2133.8   0.075       0  2232.9     0.1       0
  2349.2    0.05       0  2414.8     0.1       0  2728.1   0.075       0
  2926.3    0.05       0  3025.3     0.1       0  3822.5    0.05       0
  4981.8   0.035       0  5006.6    0.05       0  5503.6   0.075       0
  5702.4    0.05       0  6455.2   0.075       0  6467.9    0.05       0
Bank Sta=4981.8,5006.6
Exp/Cntr=0.3,0.1

Type RM Length L Ch R = 1,29282,1232,1232,1232
BEGIN DESCRIPTION:
Cedar Creek 29282.08
END DESCRIPTION:
XS GIS Cut Line= 3
      1588304.08      6858100.47      1592144.37      6858142.14
      1593671.04      6858086.62
#Sta/Elev= 30
  1156.5 1704.20  1437.6 1702.57  1536.6 1702.57  1617.5 1702.10  1650.3 1696.57
  2184.2 1684.79  2625.3 1678.37  2922.2 1675.03  3817.6 1672.60  3915.8 1666.00
  4006.3 1672.94  4807.6 1670.35  4877.6 1661.74  4987.6 1661.66  4989.9 1657.09
  4990.3 1656.09  5014.7 1657.09  5047.7 1660.82  5077.7 1670.78  5298.2 1670.44
  5397.9 1669.38  5447.9 1659.92  5478.0 1659.90  5518.0 1668.21  5801.0 1673.51
  6188.7 1691.39  6289.8 1695.46  6306.0 1695.78  6504.7 1696.51  6524.7 1696.39
#Mann=16,-1,0
  1156.5    0.05       0  1437.6   0.075       0  1536.6    0.05       0
  1650.3   0.075       0  2184.2    0.05       0  2625.3     0.1       0
  2922.2    0.05       0  3915.8    0.12       0  4006.3    0.05       0
  4989.9    0.05       0  5014.7    0.05       0  5298.2    0.05       0
  6188.7   0.075       0  6289.8     0.1       0  6306.0   0.075       0
  6504.7    0.05       0
Bank Sta=4989.9,5014.7
Exp/Cntr=0.3,0.1

Type RM Length L Ch R = 1,28050,348,348,348
BEGIN DESCRIPTION:
Cedar Creek 28050.23
END DESCRIPTION:
XS GIS Cut Line= 3
      1588831.88      6859100.47      1592477.70      6859169.91
      1593540.10      6858919.94
#Sta/Elev= 30
  1376.8 1687.29  1980.0 1669.90  2091.9 1672.06  2270.1 1668.38  2289.8 1671.78
  2330.1 1669.93  2460.1 1675.97  2680.2 1668.65  3279.5 1670.35  3612.7 1670.72
  3700.3 1664.72  3730.3 1670.59  3774.3 1671.28  4200.4 1667.65  4840.6 1668.91
  4910.6 1658.02  4961.9 1658.87  5000.6 1658.12  5041.1 1665.48  5080.1 1665.26
  5123.2 1662.21  5133.2 1655.73  5178.0 1654.73  5216.1 1655.73  5224.5 1662.69
  5319.5 1658.56  5462.3 1672.40  5536.5 1668.31  6085.9 1688.22  6114.7 1689.70
#Mann=10,-1,0
  1376.8    0.05       0  2091.9   0.075       0  2289.8    0.05       0
  3279.5    0.12       0  3774.3    0.05       0  4961.9    0.12       0
  5080.1    0.05       0  5133.2    0.07       0  5216.1    0.05       0
  6085.9   0.075       0
Bank Sta=5133.2,5216.1
Exp/Cntr=0.3,0.1

Type RM Length L Ch R = 1,27702,1425,1425,1425
BEGIN DESCRIPTION:
Cedar Creek 27702.36
END DESCRIPTION:
XS GIS Cut Line= 3
      1588838.83      6859864.36      1591942.98      6859787.97
      1593540.06      6858968.60
#Sta/Elev= 30
  1254.5 1685.70  1347.6 1685.21  1644.9 1678.65  1670.8 1674.55  1920.9 1673.81
  2041.3 1669.14  2331.0 1665.15  2399.0 1668.04  2412.0 1668.07  2591.1 1663.26
  2761.1 1669.26  3126.8 1669.13  3239.7 1669.13  3304.2 1669.22  3428.7 1669.23
  3626.8 1670.89  4822.7 1668.08  4891.0 1656.14  4968.9 1655.71  4969.6 1654.71
  5010.3 1655.71  5029.1 1662.51  5100.7 1665.82  5312.0 1668.37  5362.2 1674.31
  5534.0 1671.19  5839.0 1677.23  6011.0 1686.81  6121.4 1688.12  6154.6 1689.17
#Mann=16,-1,0
  1254.5   0.075       0  1347.6     0.1       0  1644.9    0.05       0
  2041.3    0.12       0  2399.0    0.05       0  2412.0    0.12       0
  3126.8    0.05       0  3239.7    0.12       0  3304.2    0.05       0
  3428.7    0.12       0  3626.8    0.05       0  4891.0    0.12       0
  4968.9    0.07       0  5010.3    0.12       0  5100.7    0.05       0
  6121.4   0.075       0
Bank Sta=4968.9,5010.3
Exp/Cntr=0.3,0.1

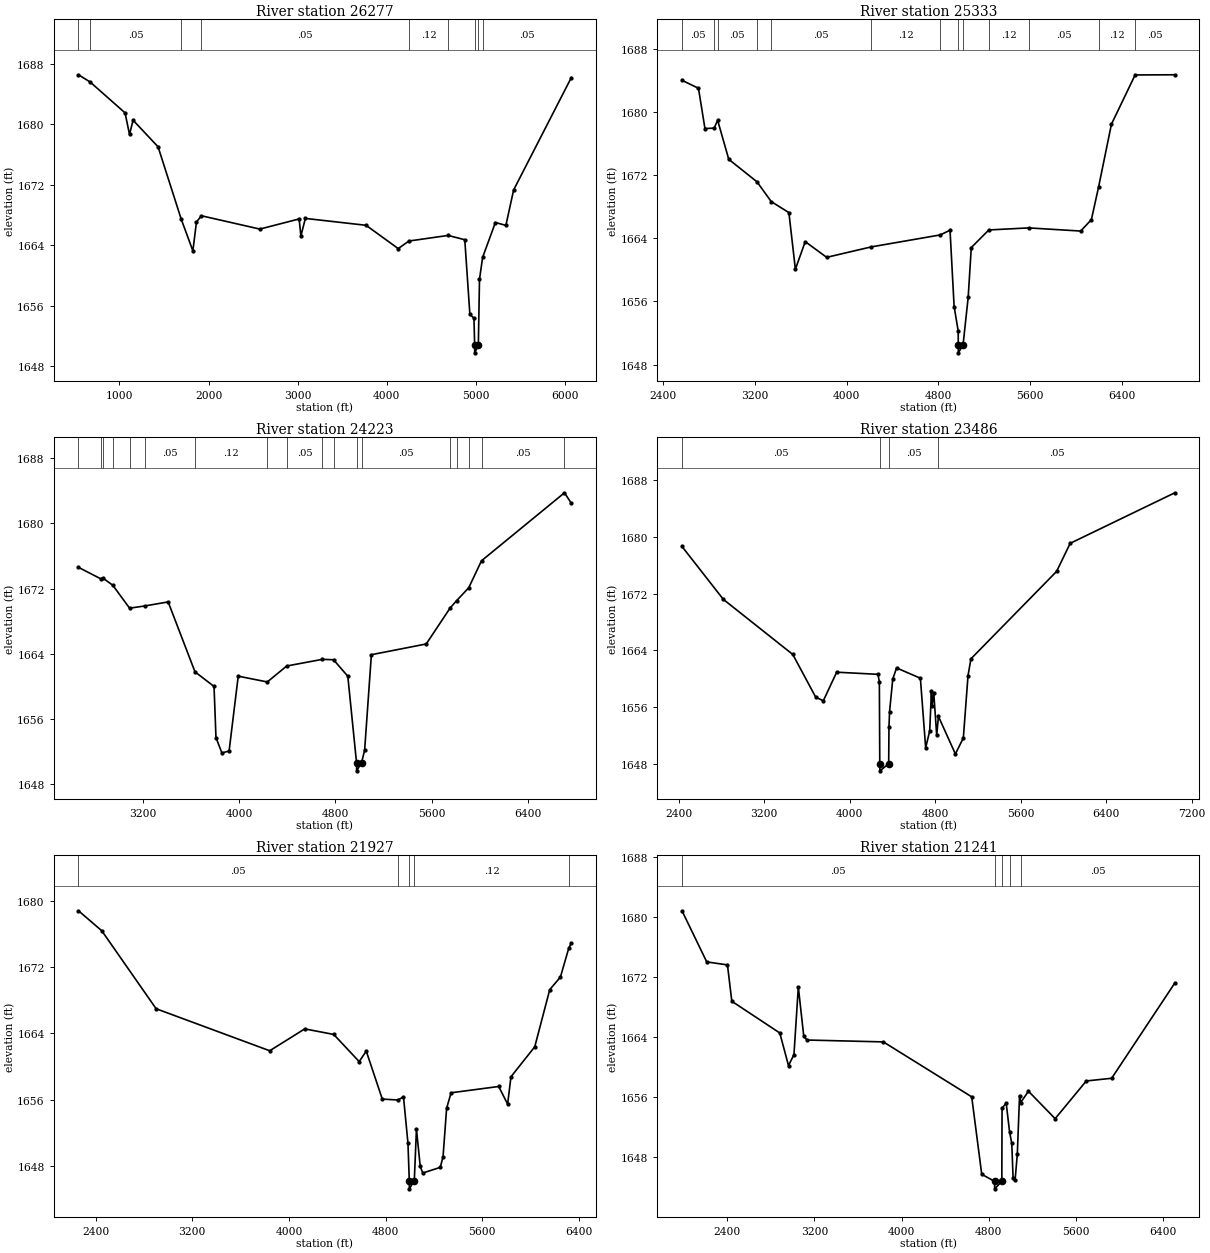
Type RM Length L Ch R = 1,26277,944,944,944
BEGIN DESCRIPTION:
Cedar Creek 26277.17
END DESCRIPTION:
XS GIS Cut Line= 3
      1588873.52      6860815.75      1592651.31      6860572.69
      1594344.02      6860142.58
#Sta/Elev= 30
   540.0 1686.56   671.2 1685.60  1062.6 1681.52  1112.7 1678.67  1152.7 1680.55
  1433.3 1677.03  1692.8 1667.47  1824.0 1663.27  1864.2 1667.09  1920.1 1667.91
  2575.7 1666.15  3016.6 1667.49  3036.6 1665.25  3086.7 1667.56  3768.1 1666.65
  4128.9 1663.57  4249.0 1664.57  4689.1 1665.31  4876.2 1664.74  4933.2 1654.89
  4979.4 1654.34  4986.8 1650.78  4987.6 1649.78  5028.3 1650.78  5041.3 1659.51
  5076.4 1662.41  5219.8 1667.02  5337.4 1666.64  5424.5 1671.33  6072.1 1686.19
#Mann=9,-1,0
   540.0   0.075       0   671.2    0.05       0  1692.8    0.12       0
  1920.1    0.05       0  4249.0    0.12       0  4689.1    0.05       0
  4986.8    0.07       0  5028.3    0.05       0  5076.4    0.05       0
Bank Sta=4986.8,5028.3
Exp/Cntr=0.3,0.1

Type RM Length L Ch R = 1,25333,1110,1110,1110
BEGIN DESCRIPTION:
Cedar Creek 25332.717
END DESCRIPTION:
XS GIS Cut Line= 3
      1591204.99      6862638.00      1593183.31      6861217.13
      1594734.62      6860190.76
#Sta/Elev= 30
  2564.3 1684.01  2708.0 1683.00  2764.4 1677.90  2844.8 1677.95  2875.0 1678.95
  2972.0 1674.00  3218.0 1671.15  3342.4 1668.64  3496.2 1667.25  3552.7 1660.07
  3638.6 1663.57  3825.3 1661.58  4213.1 1662.90  4815.9 1664.42  4900.8 1665.02
  4936.4 1655.35  4972.0 1652.24  4972.7 1650.48  4973.4 1649.48  5014.2 1650.48
  5058.9 1656.50  5086.0 1662.82  5239.2 1665.05  5586.9 1665.31  6039.9 1664.91
  6133.1 1666.36  6196.4 1670.55  6307.7 1678.45  6514.2 1684.69  6860.1 1684.71
#Mann=13,-1,0
  2564.3    0.05       0  2844.8     0.1       0  2875.0    0.05       0
  3218.0   0.075       0  3342.4    0.05       0  4213.1    0.12       0
  4815.9    0.05       0  4972.7    0.05       0  5014.2    0.05       0
  5239.2    0.12       0  5586.9    0.05       0  6196.4    0.12       0
  6514.2    0.05       0
Bank Sta=4972.7,5014.2
Exp/Cntr=0.3,0.1

Type RM Length L Ch R = 1,24223,737,737,737
BEGIN DESCRIPTION:
Cedar Creek 24222.99
END DESCRIPTION:
XS GIS Cut Line= 3
      1591838.84      6863142.12      1593887.42      6862024.08
      1595281.81      6860941.87
#Sta/Elev= 30
  2663.0 1674.60  2848.5 1673.19  2865.4 1673.29  2948.0 1672.40  3088.0 1669.58
  3217.0 1669.86  3408.7 1670.35  3631.9 1661.75  3790.3 1659.96  3806.4 1653.67
  3855.8 1651.78  3915.6 1652.02  3991.5 1661.22  4233.3 1660.51  4394.8 1662.47
  4691.4 1663.29  4784.2 1663.24  4902.9 1661.21  4975.5 1650.58  4976.2 1649.58
  5017.1 1650.58  5042.8 1652.12  5098.9 1663.86  5555.1 1665.18  5754.2 1669.61
  5808.2 1670.51  5908.5 1672.09  6014.9 1675.41  6704.9 1683.77  6761.9 1682.48
#Mann=18,-1,0
  2663.0     0.1       0  2848.5   0.075       0  2865.4     0.1       0
  2948.0   0.075       0  3088.0     0.1       0  3217.0    0.05       0
  3631.9    0.12       0  4233.3     0.1       0  4394.8    0.05       0
  4691.4   0.075       0  4784.2    0.05       0  4975.5   0.035       0
  5017.1    0.05       0  5754.2    0.12       0  5808.2    0.05       0
  5908.5    0.12       0  6014.9    0.05       0  6704.9     0.1       0
Bank Sta=4975.5,5017.1
Exp/Cntr=0.3,0.1

Type RM Length L Ch R = 1,23486,1559,1559,1559
BEGIN DESCRIPTION:
Cedar Creek 23486.06
END DESCRIPTION:
XS GIS Cut Line= 3
      1592095.78      6863815.74      1594338.81      6862586.58
      1595977.68      6861350.48
#Sta/Elev= 30
  2431.4 1678.67  2818.2 1671.21  3468.2 1663.44  3682.4 1657.42  3753.5 1656.91
  3878.7 1660.94  4264.5 1660.64  4277.8 1659.61  4281.8 1648.03  4283.3 1647.03
  4365.1 1648.03  4367.8 1653.27  4373.5 1655.39  4403.2 1659.97  4438.9 1661.54
  4661.7 1660.09  4711.1 1650.27  4749.0 1652.68  4765.1 1658.27  4770.8 1656.22
  4786.9 1657.97  4814.4 1652.05  4830.4 1654.71  4989.1 1649.41  5063.6 1651.67
  5107.3 1660.46  5134.7 1662.83  5935.9 1675.15  6062.9 1679.11  7041.9 1686.24
#Mann=4,-1,0
  2431.4    0.05       0  4281.8    0.05       0  4365.1    0.05       0
  4830.4    0.05       0
Bank Sta=4281.8,4365.1
Exp/Cntr=0.3,0.1

Type RM Length L Ch R = 1,21927,686,686,686
BEGIN DESCRIPTION:
Cedar Creek 21926.88
END DESCRIPTION:
XS GIS Cut Line= 3
      1592262.43      6863968.53      1594526.31      6863961.58
      1596088.85      6863037.95
#Sta/Elev= 30
  2258.6 1678.80  2451.2 1676.39  2901.2 1666.98  3841.2 1661.91  4131.2 1664.55
  4371.2 1663.88  4581.8 1660.60  4640.3 1661.87  4772.9 1656.08  4902.4 1655.97
  4948.5 1656.35  4985.6 1650.74  4996.3 1646.25  4997.1 1645.25  5038.0 1646.25
  5055.7 1652.46  5087.0 1647.96  5108.4 1647.16  5252.8 1647.84  5276.0 1649.15
  5305.4 1654.97  5342.5 1656.84  5736.5 1657.60  5810.4 1655.47  5837.9 1658.77
  6034.9 1662.39  6158.9 1669.28  6247.5 1670.81  6315.5 1674.25  6337.6 1674.92
#Mann=5,-1,0
  2258.6    0.05       0  4902.4    0.12       0  4996.3    0.07       0
  5038.0    0.12       0  6315.5   0.075       0
Bank Sta=4996.3,5038
Exp/Cntr=0.3,0.1

Type RM Length L Ch R = 1,21241,728,728,728
BEGIN DESCRIPTION:
Mapping XS 69dbdad7
END DESCRIPTION:
XS GIS Cut Line= 4
      1592447.87      6864239.64      1595078.06      6864213.60
      1596229.11      6863979.22      1596941.31      6863906.44
#Sta/Elev= 30
  1985.2 1680.83  2212.3 1674.01  2402.3 1673.61  2442.4 1668.76  2882.4 1664.53
  2962.4 1660.18  3012.4 1661.64  3052.4 1670.66  3102.4 1664.08  3132.4 1663.59
  3832.4 1663.34  4643.0 1656.01  4734.9 1645.68  4852.5 1644.74  4853.7 1643.74
  4919.2 1644.74  4921.4 1654.52  4959.4 1655.16  4990.3 1651.34  5010.4 1649.81
  5022.6 1645.17  5041.0 1644.92  5061.4 1648.40  5081.8 1656.19  5091.9 1655.25
  5163.5 1656.76  5408.4 1653.10  5694.1 1658.13  5926.8 1658.49  6506.1 1671.19
#Mann=5,-1,0
  1985.2    0.05       0  4852.5    0.07       0  4919.2    0.05       0
  4990.3    0.12       0  5091.9    0.05       0
Bank Sta=4852.5,4919.2
Exp/Cntr=0.3,0.1

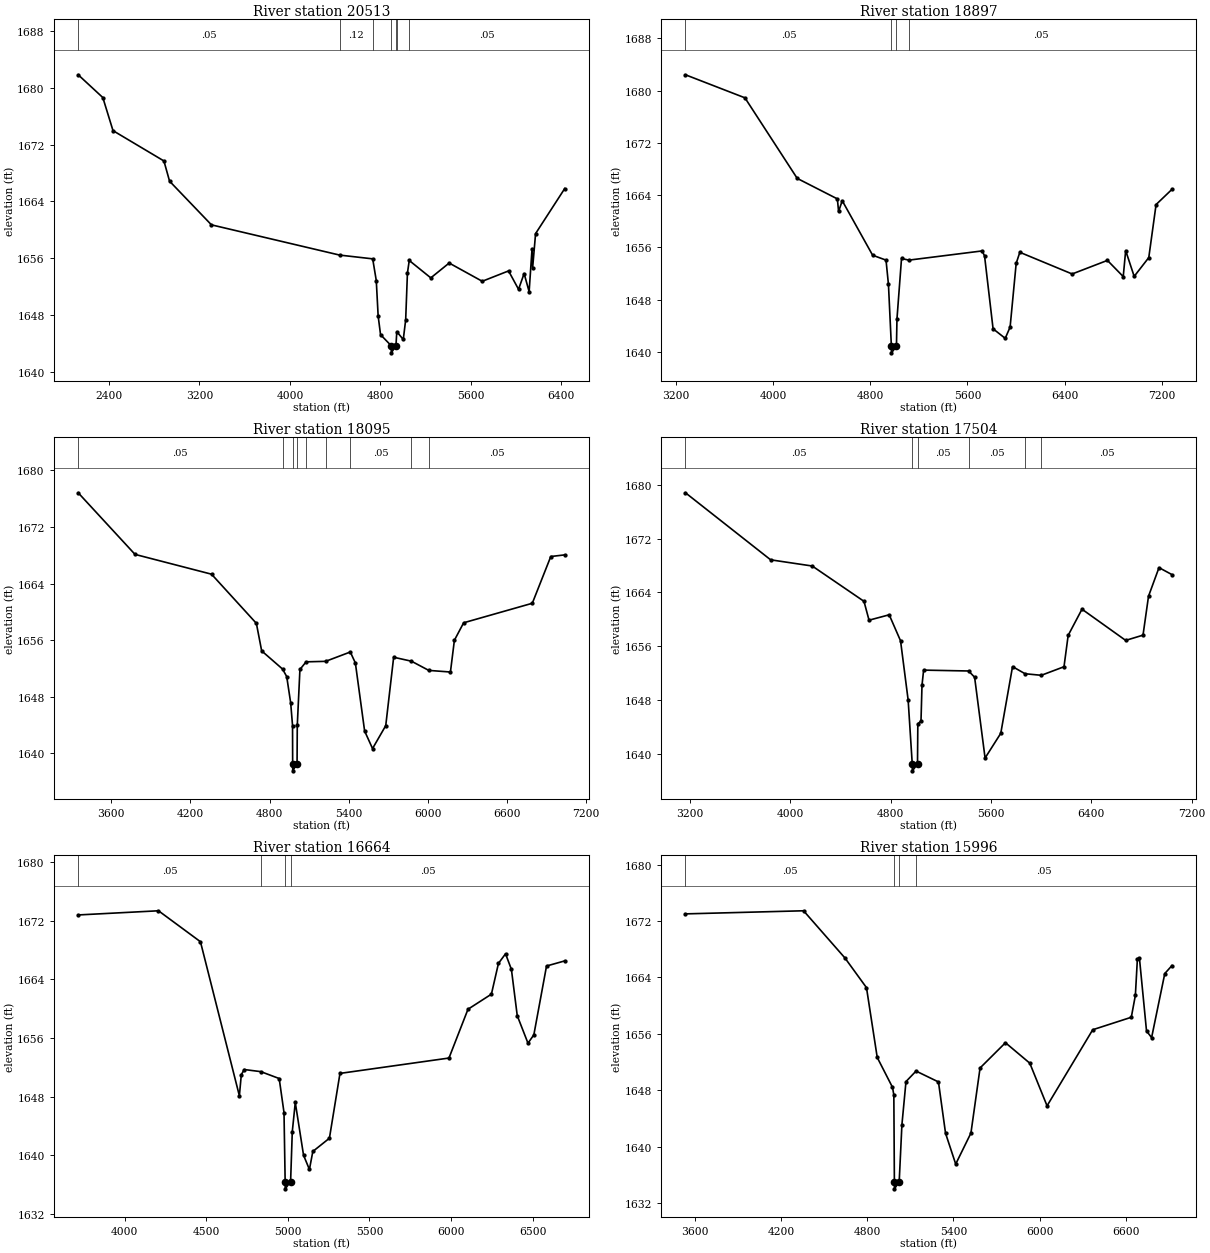
Type RM Length L Ch R = 1,20513,1616,1616,1616
BEGIN DESCRIPTION:
Cedar Creek 20513.4
END DESCRIPTION:
XS GIS Cut Line= 3
      1592547.12      6864454.64      1594762.42      6864496.30
      1596734.61      6865176.85
#Sta/Elev= 30
  2127.7 1681.84  2345.6 1678.63  2435.6 1673.97  2885.7 1669.70  2935.7 1666.85
  3305.8 1660.70  4439.3 1656.44  4731.6 1655.91  4763.2 1652.86  4779.8 1647.87
  4801.0 1645.23  4895.5 1643.67  4896.3 1642.67  4937.2 1643.67  4944.7 1645.65
  5002.0 1644.55  5023.2 1647.32  5038.7 1653.90  5054.8 1655.68  5245.3 1653.23
  5407.8 1655.32  5700.2 1652.75  5932.9 1654.21  6021.1 1651.62  6070.4 1653.84
  6114.7 1651.29  6140.6 1657.35  6145.9 1654.69  6171.8 1659.47  6429.7 1665.82
#Mann=7,-1,0
  2127.7    0.05       0  4439.3    0.12       0  4731.6    0.05       0
  4895.5    0.07       0  4937.2    0.05       0  4944.7    0.12       0
  5054.8    0.05       0
Bank Sta=4895.5,4937.2
Exp/Cntr=0.3,0.1

Type RM Length L Ch R = 1,18897,802,802,802
BEGIN DESCRIPTION:
Cedar Creek 18896.62
END DESCRIPTION:
XS GIS Cut Line= 3
      1592685.99      6865315.75      1594387.42      6865260.19
      1596686.07      6865343.53
#Sta/Elev= 30
  3280.3 1682.43  3769.6 1678.90  4199.8 1666.56  4530.0 1663.42  4540.0 1661.49
  4570.0 1663.14  4820.1 1654.79  4930.2 1654.04  4950.2 1650.31  4974.3 1640.84
  4975.0 1639.84  5016.0 1640.84  5020.2 1645.03  5057.7 1654.29  5118.1 1654.04
  5720.7 1655.45  5740.7 1654.69  5810.8 1643.52  5910.8 1642.06  5950.9 1643.79
  6000.9 1653.55  6030.9 1655.24  6461.2 1651.92  6751.4 1654.00  6881.5 1651.52
  6901.5 1655.50  6971.5 1651.55  7091.6 1654.43  7151.6 1662.55  7282.8 1664.89
#Mann=4,-1,0
  3280.3    0.05       0  4974.3    0.07       0  5016.0    0.05       0
  5118.1    0.05       0
Bank Sta=4974.3,5016
Exp/Cntr=0.3,0.1

Type RM Length L Ch R = 1,18095,591,591,591
BEGIN DESCRIPTION:
Cedar Creek 18095.15
END DESCRIPTION:
XS GIS Cut Line= 3
      1593054.05      6865947.69      1594679.09      6865919.91
      1596740.82      6865822.73
#Sta/Elev= 30
  3349.2 1676.85  3780.2 1668.14  4360.3 1665.34  4700.3 1658.39  4740.4 1654.50
  4898.8 1651.93  4930.4 1650.86  4960.4 1647.15  4974.5 1643.94  4975.4 1638.54
  4976.0 1637.54  5008.8 1638.54  5010.4 1643.95  5030.5 1651.87  5077.3 1652.95
  5225.3 1653.02  5412.4 1654.34  5450.9 1652.79  5521.0 1643.17  5581.1 1640.69
  5681.2 1643.93  5741.2 1653.60  5876.0 1653.04  6007.4 1651.74  6171.7 1651.51
  6201.7 1656.00  6271.8 1658.47  6792.4 1661.23  6932.6 1667.84  7038.5 1668.07
#Mann=9,-1,0
  3349.2    0.05       0  4898.8    0.12       0  4975.4    0.07       0
  5008.8    0.12       0  5077.3    0.05       0  5225.3    0.12       0
  5412.4    0.05       0  5876.0    0.12       0  6007.4    0.05       0
Bank Sta=4975.4,5008.8
Exp/Cntr=0.3,0.1

Type RM Length L Ch R = 1,17504,840,840,840
BEGIN DESCRIPTION:
Cedar Creek 17504.21
END DESCRIPTION:
XS GIS Cut Line= 3
      1592949.88      6866662.98      1594762.42      6866461.58
      1596734.66      6865878.24
#Sta/Elev= 30
  3162.5 1678.80  3841.8 1668.85  4173.8 1667.93  4586.3 1662.69  4626.6 1659.89
  4787.4 1660.69  4877.9 1656.83  4938.5 1648.04  4971.3 1638.53  4972.1 1637.53
  5013.1 1638.53  5015.7 1644.49  5041.0 1644.94  5049.0 1650.24  5061.9 1652.48
  5420.9 1652.35  5468.6 1651.42  5552.0 1639.43  5677.2 1643.10  5771.0 1653.00
  5871.1 1651.94  6000.4 1651.71  6181.4 1652.98  6214.7 1657.64  6324.9 1661.52
  6673.3 1656.89  6811.6 1657.67  6855.5 1663.45  6939.0 1667.69  7042.9 1666.65
#Mann=6,-1,0
  3162.5    0.05       0  4971.3   0.035       0  5013.1    0.05       0
  5420.9    0.05       0  5871.1    0.12       0  6000.4    0.05       0
Bank Sta=4971.3,5013.1
Exp/Cntr=0.3,0.1

Type RM Length L Ch R = 1,16664,668,668,668
BEGIN DESCRIPTION:
Cedar Creek 16664.12
END DESCRIPTION:
XS GIS Cut Line= 3
      1594269.36      6867315.75      1595484.65      6866822.69
      1596859.64      6865878.25
#Sta/Elev= 30
  3716.2 1672.82  4207.9 1673.39  4464.9 1669.16  4703.3 1648.10  4715.1 1650.98
  4732.8 1651.69  4834.8 1651.40  4947.1 1650.46  4976.6 1645.81  4983.6 1636.38
  4984.2 1635.38  5017.0 1636.38  5027.3 1643.20  5045.6 1647.19  5096.3 1639.97
  5132.2 1638.03  5153.1 1640.49  5254.7 1642.30  5319.3 1651.16  5986.8 1653.26
  6103.2 1659.93  6246.6 1661.99  6289.8 1666.20  6333.2 1667.51  6369.1 1665.38
  6404.9 1659.05  6470.6 1655.29  6506.5 1656.43  6584.2 1665.84  6695.8 1666.54
#Mann=4,-1,0
  3716.2    0.05       0  4834.8    0.12       0  4983.6    0.07       0
  5017.0    0.05       0
Bank Sta=4983.6,5017
Exp/Cntr=0.3,0.1

Type RM Length L Ch R = 1,15996,1007,1007,1007
BEGIN DESCRIPTION:
Cedar Creek 15995.86
END DESCRIPTION:
XS GIS Cut Line= 3
      1594199.89      6867871.32      1595540.20      6867267.14
      1596915.17      6865926.89
#Sta/Elev= 30
  3532.4 1673.02  4355.4 1673.46  4644.0 1666.76  4793.8 1662.56  4868.7 1652.66
  4975.0 1648.43  4984.4 1647.35  4988.2 1635.03  4988.8 1634.03  5021.7 1635.03
  5040.7 1643.13  5069.0 1649.24  5139.1 1650.73  5295.3 1649.19  5344.7 1641.91
  5415.5 1637.54  5521.6 1641.94  5585.2 1651.17  5762.1 1654.75  5931.7 1651.85
  6052.0 1645.80  6370.2 1656.59  6639.0 1658.36  6667.3 1661.46  6681.4 1666.63
  6695.5 1666.77  6745.0 1656.42  6780.4 1655.47  6872.3 1664.56  6922.7 1665.70
#Mann=4,-1,0
  3532.4    0.05       0  4988.2    0.05       0  5021.7    0.05       0
  5139.1    0.05       0
Bank Sta=4988.2,5021.7
Exp/Cntr=0.3,0.1