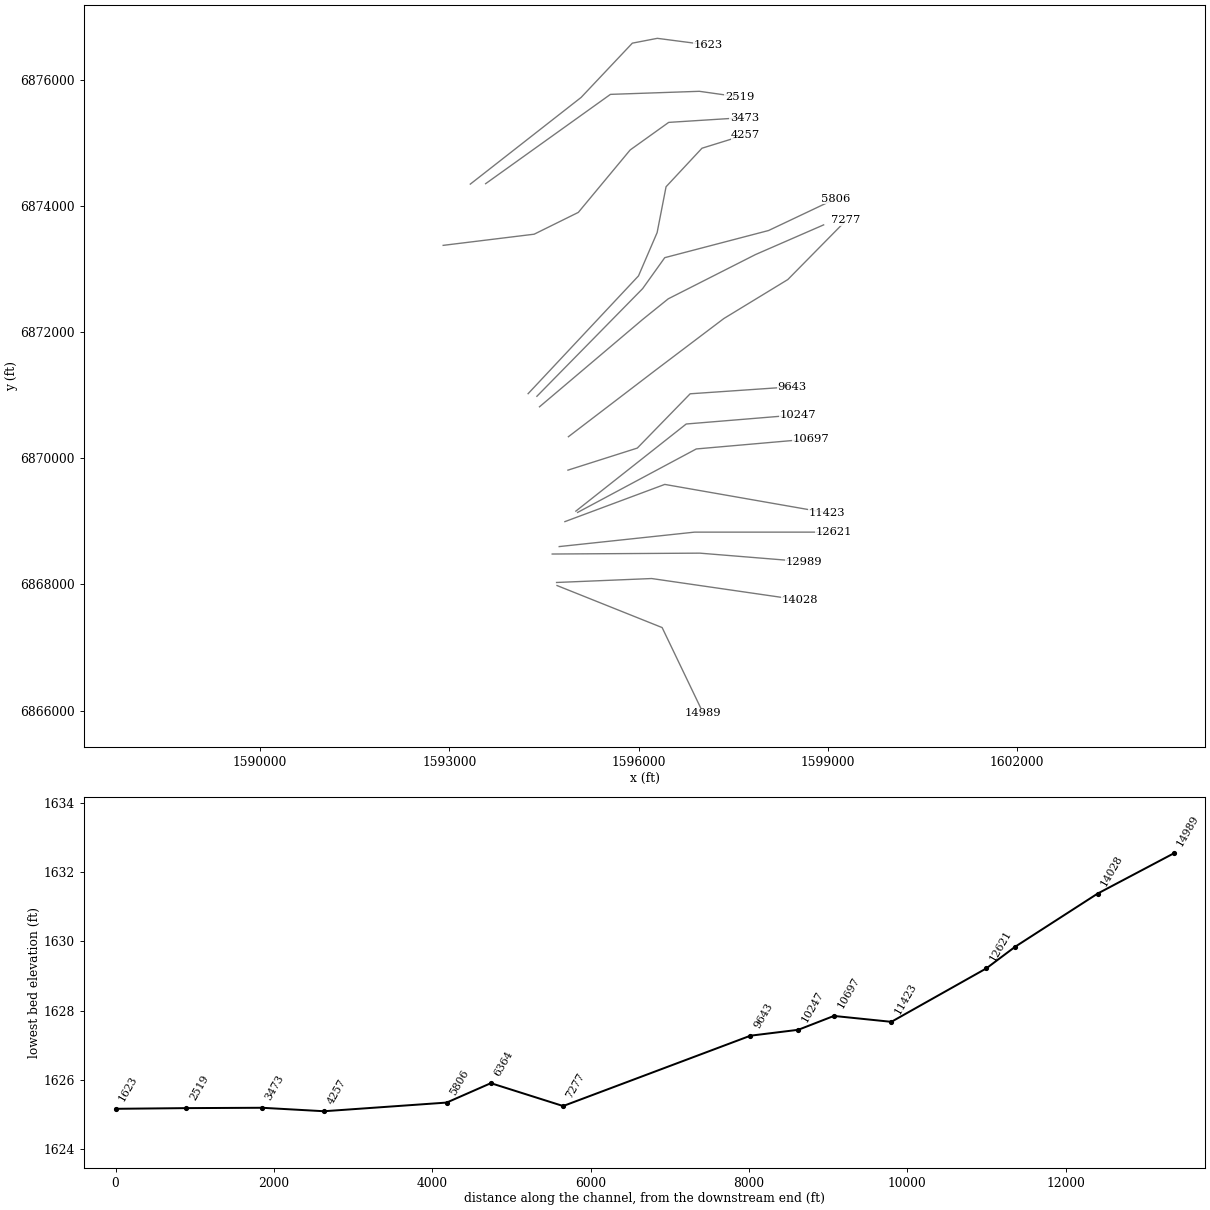
HEC-RAS study Cedar Creek.prj: Cedar Creek Base Level Engineering

--- Cedar Creek.g01 (geometry) --- (continued)

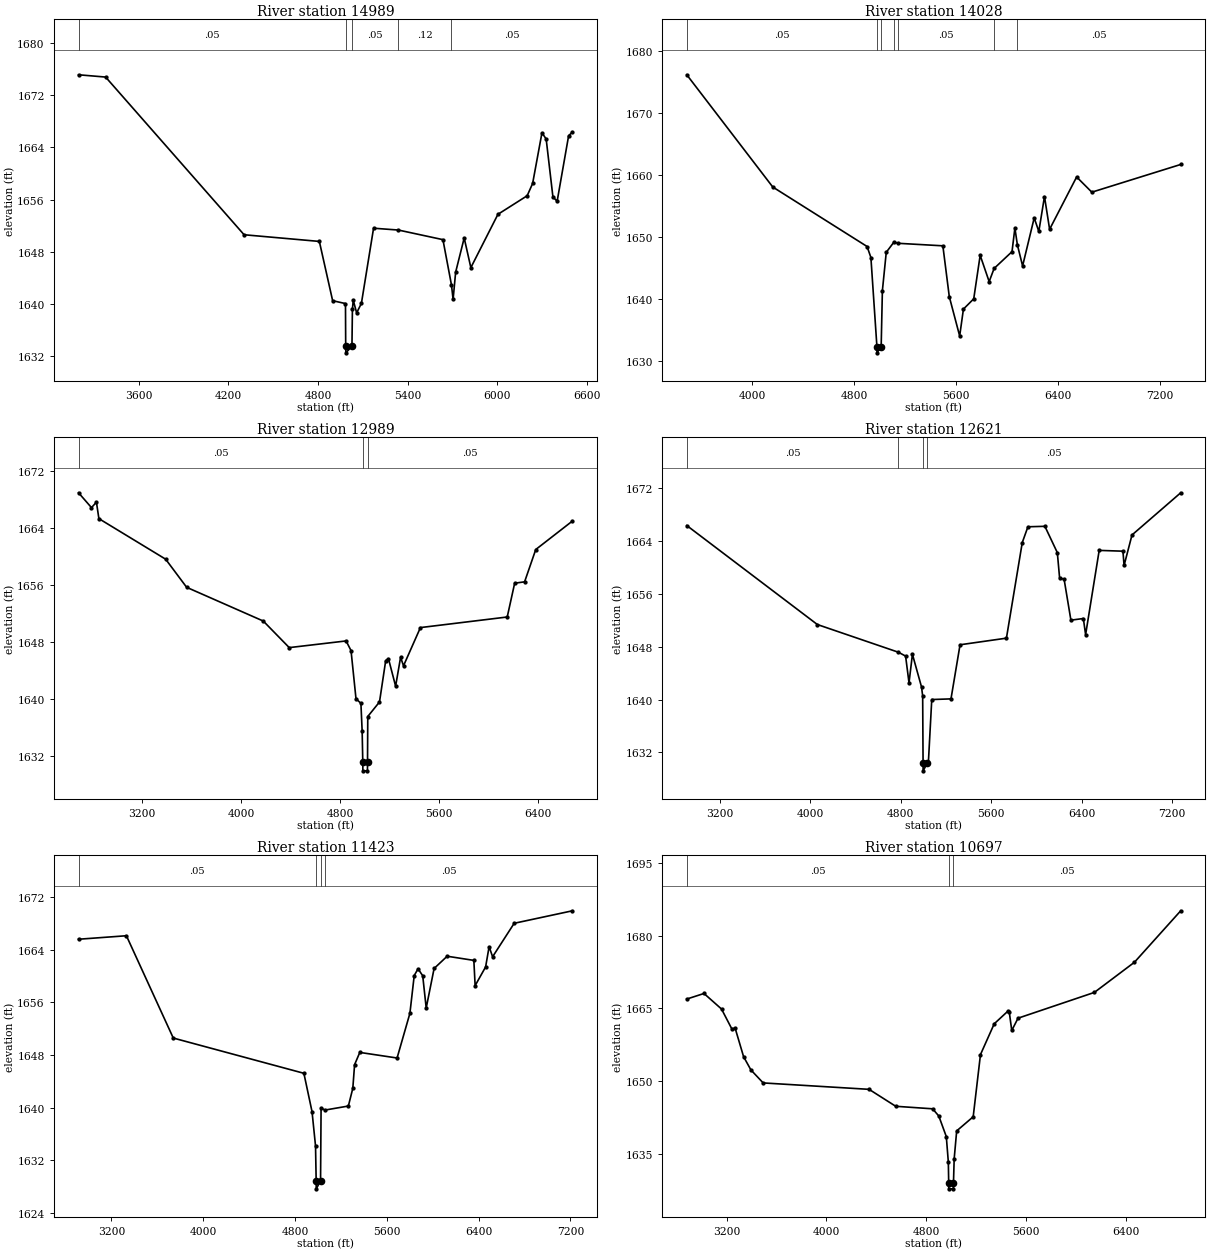
Type RM Length L Ch R = 1,14989,961,961,961
BEGIN DESCRIPTION:
Cedar Creek 14989.38
END DESCRIPTION:
XS GIS Cut Line= 3
      1594706.89      6867982.40      1596373.53      6867315.75
      1597026.32      6865954.62
#Sta/Elev= 30
  3198.8 1675.09  3379.9 1674.74  4306.3 1650.61  4809.8 1649.59  4898.7 1640.52
  4984.6 1640.08  4986.1 1633.54  4986.8 1632.54  5027.9 1633.54  5031.0 1639.22
  5036.6 1640.59  5059.2 1638.66  5091.1 1640.10  5172.5 1651.61  5338.7 1651.33
  5636.6 1649.86  5693.7 1642.93  5704.6 1640.73  5721.7 1644.89  5778.8 1650.12
  5823.4 1645.58  6004.6 1653.74  6200.2 1656.58  6236.7 1658.46  6299.1 1666.21
  6327.3 1665.26  6372.6 1656.37  6400.8 1655.75  6477.5 1665.76  6503.4 1666.34
#Mann=5,-1,0
  3198.8    0.05       0  4986.1    0.05       0  5027.9    0.05       0
  5338.7    0.12       0  5693.7    0.05       0
Bank Sta=4986.1,5027.9
Exp/Cntr=0.3,0.1

Type RM Length L Ch R = 1,14028,1039,1039,1039
BEGIN DESCRIPTION:
Cedar Creek 14027.31
END DESCRIPTION:
XS GIS Cut Line= 3
      1594699.95      6868031.03      1596206.87      6868093.53
      1598554.12      6867753.24
#Sta/Elev= 30
  3486.0 1676.12  4161.6 1658.06  4902.3 1648.49  4932.3 1646.72  4979.6 1632.38
  4980.2 1631.38  5013.0 1632.38  5022.6 1641.40  5053.0 1647.56  5115.0 1649.24
  5141.6 1649.01  5497.6 1648.60  5548.1 1640.42  5629.6 1634.09  5659.2 1638.42
  5740.1 1640.07  5790.6 1647.07  5861.3 1642.84  5900.2 1644.96  6040.8 1647.66
  6063.4 1651.46  6082.9 1648.76  6124.0 1645.36  6215.0 1653.09  6251.4 1650.91
  6295.8 1656.53  6336.2 1651.26  6548.4 1659.68  6667.7 1657.23  7366.0 1661.69
#Mann=7,-1,0
  3486.0    0.05       0  4979.6    0.05       0  5013.0    0.05       0
  5115.0    0.12       0  5141.6    0.05       0  5900.2    0.12       0
  6082.9    0.05       0
Bank Sta=4979.6,5013
Exp/Cntr=0.3,0.1

Type RM Length L Ch R = 1,12989,368,368,368
BEGIN DESCRIPTION:
Cedar Creek 12988.67
END DESCRIPTION:
XS GIS Cut Line= 3
      1594630.45      6868482.41      1596970.76      6868496.30
      1598621.36      6868362.07
#Sta/Elev= 30
  2685.0 1669.00  2789.6 1666.91  2829.6 1667.68  2849.6 1665.36  3389.6 1659.65
  3559.6 1655.69  4179.6 1650.94  4389.6 1647.20  4849.6 1648.14  4889.6 1646.78
  4929.6 1640.02  4969.6 1639.34  4979.6 1635.41  4984.7 1631.05  4985.3 1629.85
  5022.4 1629.85  5023.0 1631.05  5025.0 1637.50  5119.9 1639.55  5170.1 1645.37
  5192.3 1645.65  5250.3 1641.77  5290.5 1645.84  5314.2 1644.64  5451.0 1650.02
  6153.3 1651.51  6213.5 1656.27  6293.8 1656.46  6384.1 1661.01  6681.4 1665.03
#Mann=3,-1,0
  2685.0    0.05       0  4984.7   0.035       0  5023.0    0.05       0
Bank Sta=4984.7,5023
Exp/Cntr=0.3,0.1

Type RM Length L Ch R = 1,12621,1198,1198,1198
BEGIN DESCRIPTION:
Cedar Creek 12621.05
END DESCRIPTION:
XS GIS Cut Line= 3
      1594741.62      6868600.47      1596887.42      6868829.64
      1599095.72      6868829.64
#Sta/Elev= 30
  2910.4 1666.31  4064.8 1651.34  4781.4 1647.15  4844.7 1646.57  4874.9 1642.53
  4905.1 1646.84  4985.5 1641.90  4995.6 1640.55  4999.2 1630.42  4999.8 1629.22
  5037.5 1630.42  5045.9 1630.42  5076.0 1640.00  5246.0 1640.10  5326.0 1648.28
  5736.0 1649.28  5876.0 1663.73  5926.0 1666.12  6076.0 1666.19  6186.0 1662.21
  6206.0 1658.39  6246.0 1658.18  6306.0 1652.00  6416.0 1652.25  6436.0 1649.81
  6556.0 1662.55  6766.0 1662.43  6776.0 1660.27  6846.0 1664.88  7276.7 1671.26
#Mann=4,-1,0
  2910.4    0.05       0  4781.4    0.12       0  4999.2    0.07       0
  5037.5    0.05       0
Bank Sta=4999.2,5037.5
Exp/Cntr=0.3,0.1

Type RM Length L Ch R = 1,11423,726,726,726
BEGIN DESCRIPTION:
Cedar Creek 11423.17
END DESCRIPTION:
XS GIS Cut Line= 3
      1594831.84      6868996.29      1596415.20      6869586.58
      1598990.76      6869135.34
#Sta/Elev= 30
  2914.0 1665.57  3331.1 1666.10  3739.6 1650.57  4877.7 1645.22  4948.8 1639.39
  4979.2 1634.19  4984.8 1628.88  4985.4 1627.68  5023.0 1628.88  5027.6 1639.92
  5062.4 1639.64  5265.3 1640.25  5304.1 1642.94  5319.6 1646.53  5365.0 1648.39
  5689.9 1647.54  5801.6 1654.32  5839.3 1660.06  5872.6 1661.08  5913.3 1660.03
  5943.7 1655.13  6012.5 1661.13  6126.3 1662.99  6358.9 1662.36  6370.1 1658.53
  6461.5 1661.37  6491.9 1664.44  6522.4 1662.91  6710.4 1667.99  7218.6 1669.89
#Mann=4,-1,0
  2914.0    0.05       0  4984.8   0.035       0  5023.0    0.05       0
  5062.4    0.05       0
Bank Sta=4984.8,5023
Exp/Cntr=0.3,0.1

Type RM Length L Ch R = 1,10697,450,450,450
BEGIN DESCRIPTION:
Cedar Creek 10696.55
END DESCRIPTION:
XS GIS Cut Line= 3
      1595033.29      6869142.15      1596915.20      6870149.08
      1598734.64      6870308.80
#Sta/Elev= 30
  2880.5 1666.93  3018.5 1668.08  3159.1 1664.88  3241.2 1660.81  3268.8 1660.90
  3336.1 1655.06  3394.7 1652.34  3493.1 1649.66  4342.3 1648.34  4556.1 1644.85
  4851.9 1644.33  4901.4 1642.85  4961.6 1638.61  4977.9 1633.36  4980.8 1629.05
  4981.4 1627.85  5018.5 1627.85  5019.1 1629.05  5024.7 1634.02  5044.8 1639.78
  5177.2 1642.69  5235.5 1655.49  5345.9 1661.84  5456.3 1664.46  5466.4 1664.28
  5486.5 1660.46  5536.7 1662.99  6149.0 1668.30  6470.2 1674.51  6841.3 1685.11
#Mann=3,-1,0
  2880.5    0.05       0  4980.8    0.05       0  5019.1    0.05       0
Bank Sta=4980.8,5019.1
Exp/Cntr=0.3,0.1

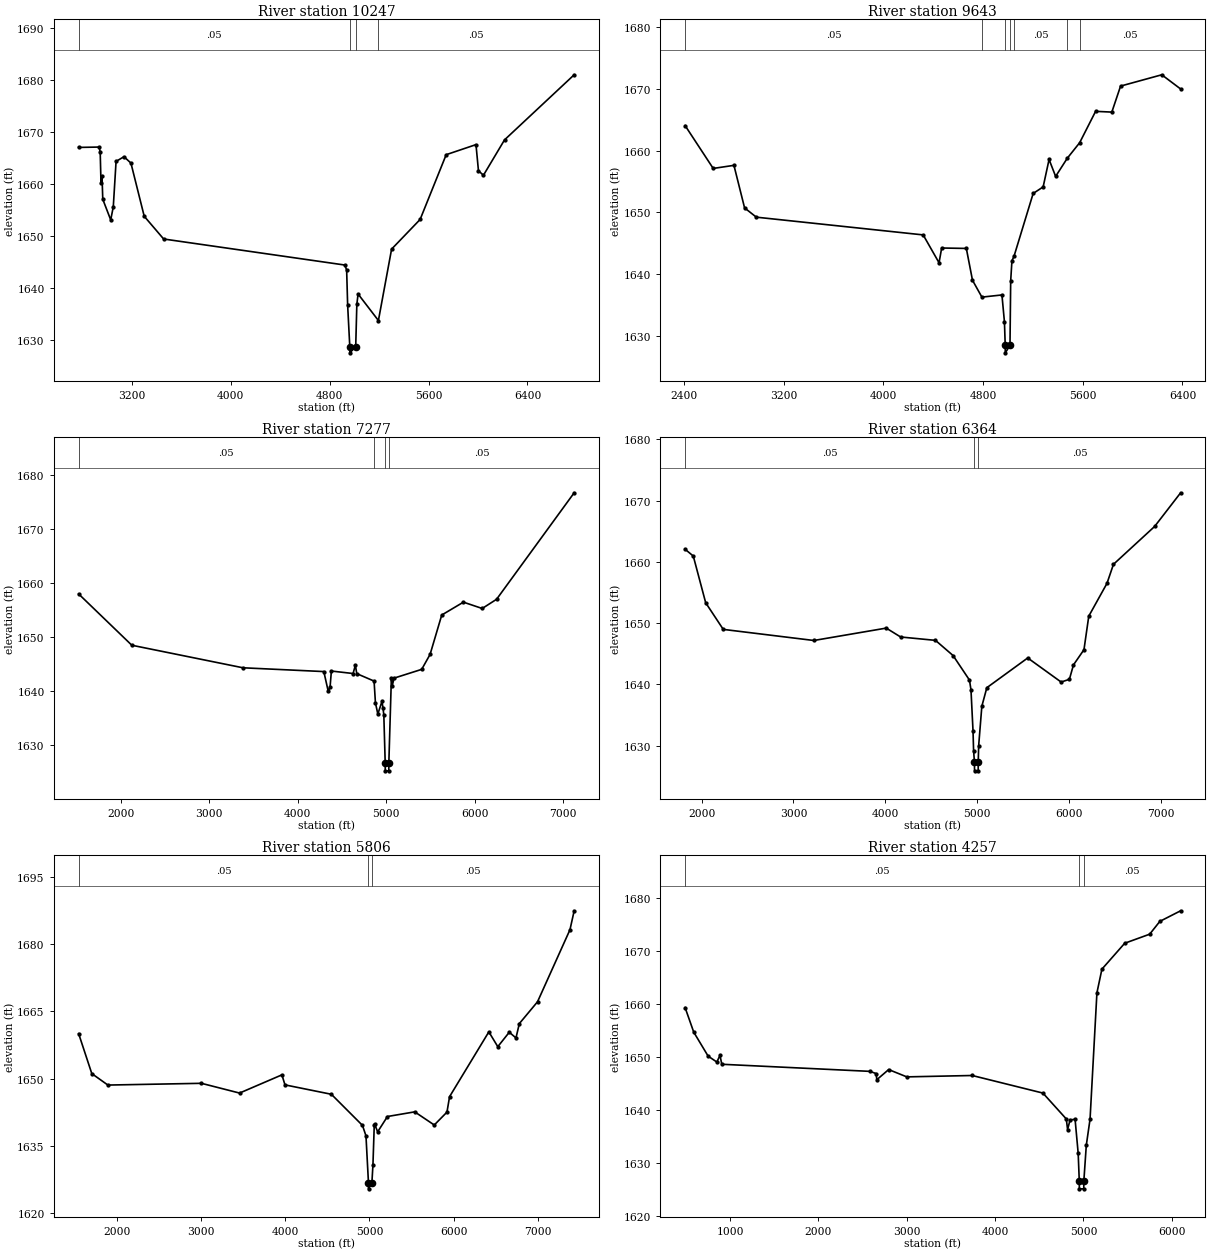
Type RM Length L Ch R = 1,10247,604,604,604
BEGIN DESCRIPTION:
Cedar Creek 10246.72
END DESCRIPTION:
XS GIS Cut Line= 3
      1595005.51      6869162.99      1596755.48      6870544.91
      1598526.26      6870690.74
#Sta/Elev= 30
  2771.1 1667.04  2937.5 1667.11  2945.5 1666.09  2951.9 1660.24  2960.0 1661.58
  2966.3 1657.05  3030.5 1653.07  3051.3 1655.59  3073.8 1664.35  3137.9 1665.25
  3194.0 1664.02  3301.4 1653.77  3458.5 1649.39  4923.9 1644.37  4938.1 1643.40
  4946.2 1636.60  4963.5 1628.65  4964.2 1627.45  5011.4 1628.65  5020.5 1636.79
  5030.5 1638.79  5194.9 1633.68  5301.5 1647.44  5532.2 1653.16  5742.9 1665.64
  5983.8 1667.58  6003.8 1662.55  6044.0 1661.67  6214.5 1668.49  6777.7 1681.04
#Mann=4,-1,0
  2771.1    0.05       0  4963.5    0.07       0  5011.4    0.05       0
  5194.9    0.05       0
Bank Sta=4963.5,5011.4
Exp/Cntr=0.3,0.1

Type RM Length L Ch R = 1,9643,2366,2366,2366
BEGIN DESCRIPTION:
Cedar Creek 9761.626
END DESCRIPTION:
XS GIS Cut Line= 4
      1594880.01      6869813.00      1595980.00      6870163.00
      1596817.98      6871024.08      1598436.01      6871135.19
#Sta/Elev= 30
  2407.7 1664.07  2633.3 1657.13  2799.7 1657.63  2885.2 1650.74  2979.6 1649.24
  4318.7 1646.37  4446.1 1641.86  4467.2 1644.25  4665.2 1644.18  4714.6 1639.03
  4790.1 1636.30  4951.0 1636.65  4971.1 1632.28  4977.3 1628.48  4977.9 1627.28
  5015.6 1628.48  5021.2 1638.94  5031.2 1642.17  5047.9 1642.91  5201.6 1653.08
  5281.8 1654.14  5329.3 1658.58  5382.0 1655.84  5475.8 1658.79  5574.8 1661.29
  5702.8 1666.37  5833.1 1666.25  5903.3 1670.46  6234.0 1672.29  6385.4 1669.99
#Mann=7,-1,0
  2407.7    0.05       0  4790.1    0.12       0  4977.3    0.07       0
  5015.6    0.12       0  5047.9    0.05       0  5475.8    0.12       0
  5574.8    0.05       0
Bank Sta=4977.3,5015.6
Exp/Cntr=0.3,0.1

Type RM Length L Ch R = 1,7277,913,913,913
BEGIN DESCRIPTION:
Mapping XS e46fdce9
END DESCRIPTION:
XS GIS Cut Line= 5
      1594887.28      6870343.13      1596269.25      6871398.71
      1597352.59      6872218.16      1598366.48      6872836.21
      1599289.67      6873773.29
#Sta/Elev= 30
  1523.7 1657.97  2124.8 1648.48  3381.2 1644.31  4294.7 1643.61  4344.6 1639.95
  4365.4 1640.78  4380.0 1643.71  4625.4 1643.25  4651.3 1644.80  4666.8 1643.23
  4862.6 1641.85  4877.9 1637.83  4905.1 1635.75  4951.4 1638.08  4963.5 1636.90
  4972.8 1635.55  4988.4 1626.65  4989.0 1625.25  5028.7 1625.25  5029.3 1626.65
  5058.0 1642.35  5067.6 1641.00  5089.0 1642.40  5400.8 1644.02  5495.6 1646.79
  5627.3 1654.07  5872.3 1656.45  6084.5 1655.28  6247.0 1656.98  7123.9 1676.68
#Mann=4,-1,0
  1523.7    0.05       0  4862.6    0.12       0  4988.4    0.07       0
  5029.3    0.05       0
Bank Sta=4988.4,5029.3
Exp/Cntr=0.3,0.1

Type RM Length L Ch R = 1,6364,558,558,558
BEGIN DESCRIPTION:
Mapping XS 91cffb88
END DESCRIPTION:
XS GIS Cut Line= 5
      1594429.23      6870817.77      1596065.87      6872204.23
      1596470.64      6872530.66      1597852.59      6873232.05
      1598934.46      6873703.63
#Sta/Elev= 30
  1821.0 1662.05  1910.1 1660.94  2045.2 1653.32  2236.4 1648.98  3222.9 1647.17
  4010.8 1649.19  4167.5 1647.74  4546.9 1647.19  4738.7 1644.71  4917.0 1640.71
  4933.4 1639.12  4955.7 1632.38  4961.8 1629.17  4971.4 1627.31  4972.0 1625.91
  5011.8 1625.91  5012.4 1627.31  5016.9 1629.98  5051.6 1636.44  5105.9 1639.47
  5551.2 1644.32  5915.1 1640.39  6004.8 1640.84  6049.2 1643.19  6163.5 1645.67
  6215.8 1651.14  6414.1 1656.49  6484.4 1659.59  6932.9 1665.77  7215.9 1671.26
#Mann=3,-1,0
  1821.0    0.05       0  4971.4    0.05       0  5012.4    0.05       0
Bank Sta=4971.4,5012.4
Exp/Cntr=0.3,0.1

Type RM Length L Ch R = 1,5806,1549,1549,1549
BEGIN DESCRIPTION:
Mapping XS 992d7489
END DESCRIPTION:
XS GIS Cut Line= 5
      1594387.57      6870984.43      1596064.41      6872692.49
      1596415.09      6873183.44      1598060.92      6873613.99
      1599130.14      6874120.83
#Sta/Elev= 30
  1548.5 1660.05  1704.8 1651.11  1895.7 1648.55  3005.9 1648.94  3458.5 1646.76
  3961.1 1650.83  3997.6 1648.59  4548.0 1646.49  4917.4 1639.53  4958.8 1637.20
  4988.3 1626.75  4988.9 1625.35  5029.3 1626.75  5041.5 1630.66  5057.2 1639.58
  5062.3 1639.75  5097.6 1638.10  5213.7 1641.52  5537.6 1642.56  5769.4 1639.62
  5920.1 1642.50  5951.1 1645.96  6417.1 1660.44  6523.4 1657.13  6659.8 1660.36
  6739.1 1659.08  6779.0 1662.29  6994.8 1667.16  7379.9 1683.27  7429.9 1687.51
#Mann=3,-1,0
  1548.5    0.05       0  4988.3    0.05       0  5029.3    0.05       0
Bank Sta=4988.3,5029.3
Exp/Cntr=0.3,0.1

Type RM Length L Ch R = 1,4257,784,784,784
BEGIN DESCRIPTION:
Mapping XS dce9490f
END DESCRIPTION:
XS GIS Cut Line= 6
      1594248.73      6871026.16      1595998.71      6872894.18
      1596294.12      6873580.95      1596435.92      6874308.44
      1597005.37      6874919.55      1597699.80      6875134.82
#Sta/Elev= 30
   490.2 1659.32   588.1 1654.68   750.8 1650.16   849.5 1649.04   885.1 1650.29
   906.1 1648.62  2583.0 1647.28  2653.9 1646.86  2660.7 1645.70  2795.0 1647.62
  3000.3 1646.24  3740.9 1646.50  4541.7 1643.18  4806.6 1638.29  4820.8 1636.30
  4849.1 1638.10  4905.8 1638.24  4941.0 1631.79  4953.5 1626.50  4954.2 1625.10
  5004.0 1625.10  5004.7 1626.50  5032.8 1633.32  5075.3 1638.26  5153.1 1662.11
  5209.7 1666.58  5467.8 1671.47  5750.5 1673.18  5865.6 1675.60  6101.0 1677.60
#Mann=3,-1,0
   490.2    0.05       0  4953.5    0.05       0  5004.7    0.05       0
Bank Sta=4953.5,5004.7
Exp/Cntr=0.3,0.1

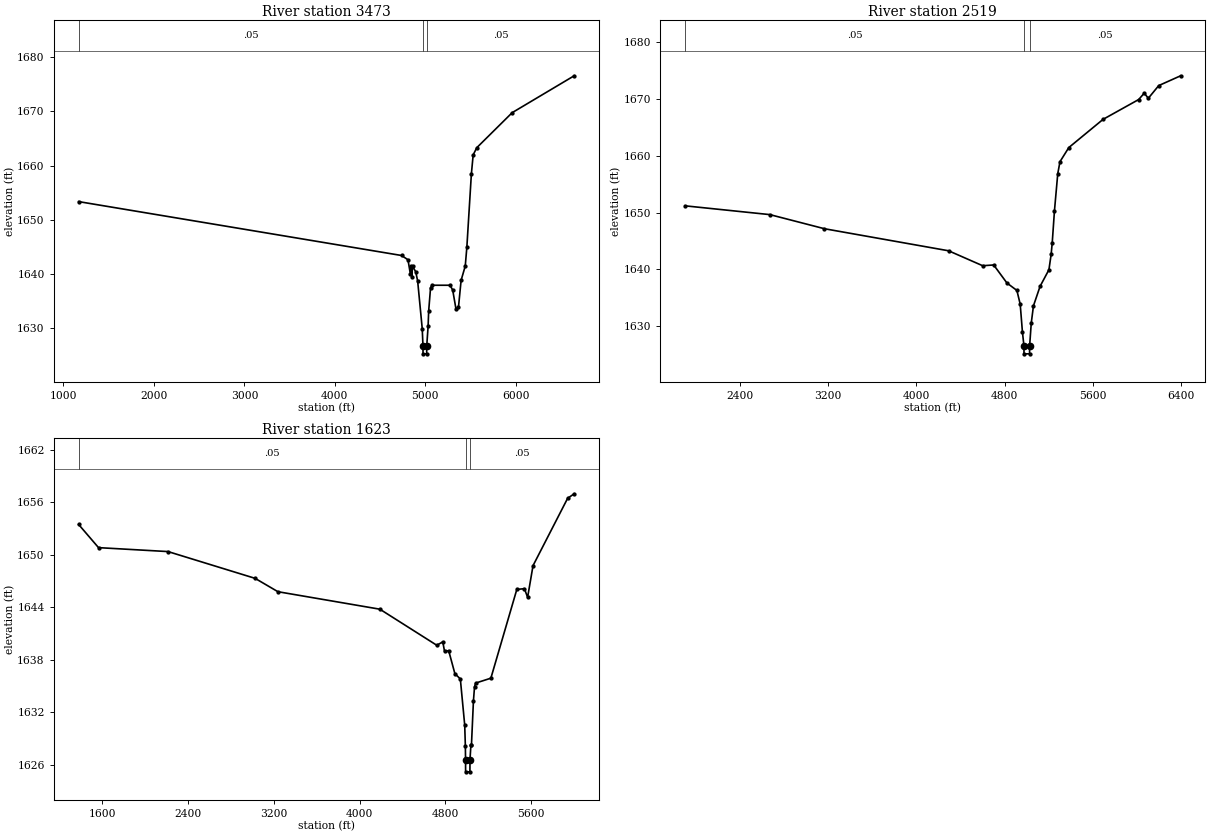
Type RM Length L Ch R = 1,3473,954,954,954
BEGIN DESCRIPTION:
Mapping XS 0992bb36
END DESCRIPTION:
XS GIS Cut Line= 6
      1592901.53      6873378.56      1594344.19      6873555.64
      1595044.68      6873901.58      1595866.48      6874891.77
      1596477.59      6875329.27      1597678.95      6875405.66
#Sta/Elev= 30
  1168.0 1653.34  4736.9 1643.38  4808.2 1642.59  4835.3 1639.87  4843.9 1641.46
  4850.0 1639.42  4858.6 1641.39  4894.2 1640.35  4915.1 1638.65  4965.5 1629.88
  4973.9 1626.60  4974.5 1625.20  5014.6 1625.20  5015.2 1626.60  5030.6 1630.31
  5036.7 1633.10  5057.6 1637.41  5072.4 1637.88  5273.8 1637.88  5302.6 1636.97
  5338.9 1633.46  5366.0 1633.79  5395.4 1638.80  5441.1 1641.43  5458.6 1644.87
  5508.7 1658.45  5528.7 1661.99  5568.8 1663.31  5959.6 1669.78  6644.9 1676.60
#Mann=3,-1,0
  1168.0    0.05       0  4973.9    0.05       0  5015.2    0.05       0
Bank Sta=4973.9,5015.2
Exp/Cntr=0.3,0.1

Type RM Length L Ch R = 1,2519,896,896,896
BEGIN DESCRIPTION:
Mapping XS d13fbe85
END DESCRIPTION:
XS GIS Cut Line= 4
      1593574.79      6874357.03      1595553.98      6875773.71
      1596963.70      6875822.32      1597601.34      6875732.22
#Sta/Elev= 30
  1905.5 1651.17  2673.0 1649.63  3168.1 1647.15  4292.2 1643.28  4600.6 1640.66
  4700.7 1640.79  4820.8 1637.62  4910.8 1636.32  4940.8 1633.91  4960.9 1629.04
  4974.6 1626.59  4975.3 1625.19  5025.6 1625.19  5026.3 1626.59  5040.9 1630.58
  5060.9 1633.62  5121.0 1637.05  5201.0 1639.95  5221.0 1642.64  5231.0 1644.70
  5251.0 1650.28  5281.0 1656.82  5301.1 1658.92  5381.1 1661.40  5691.3 1666.35
  6013.9 1669.83  6064.4 1670.95  6101.2 1670.05  6195.7 1672.28  6394.0 1674.00
#Mann=3,-1,0
  1905.5    0.05       0  4974.6    0.05       0  5026.3    0.05       0
Bank Sta=4974.6,5026.3
Exp/Cntr=0.3,0.1

Type RM Length L Ch R = 1,1623,0,0,0
BEGIN DESCRIPTION:
Cedar Creek 0
END DESCRIPTION:
XS GIS Cut Line= 5
      1593331.73      6874350.08      1595088.70      6875725.10
      1595901.20      6876586.21      1596297.03      6876662.60
      1597095.65      6876558.43
#Sta/Elev= 30
  1377.5 1653.46  1563.2 1650.81  2211.6 1650.36  3023.6 1647.30  3237.0 1645.77
  4188.2 1643.77  4718.6 1639.65  4775.2 1640.03  4791.6 1638.95  4830.1 1639.03
  4888.0 1636.40  4938.9 1635.79  4979.7 1630.52  4985.7 1628.14  4987.5 1626.57
  4988.1 1625.17  5028.3 1625.17  5028.9 1626.57  5037.5 1628.21  5042.6 1628.23
  5061.1 1633.28  5071.3 1634.89  5081.5 1635.32  5223.8 1635.88  5465.9 1646.03
  5536.4 1646.12  5566.7 1645.13  5617.1 1648.75  5939.8 1656.45  6001.0 1656.97
#Mann=3,-1,0
  1377.5    0.05       0  4987.5    0.05       0  5028.9    0.05       0
Bank Sta=4987.5,5028.9
Exp/Cntr=0.3,0.1

Chan Stop Cuts=-1