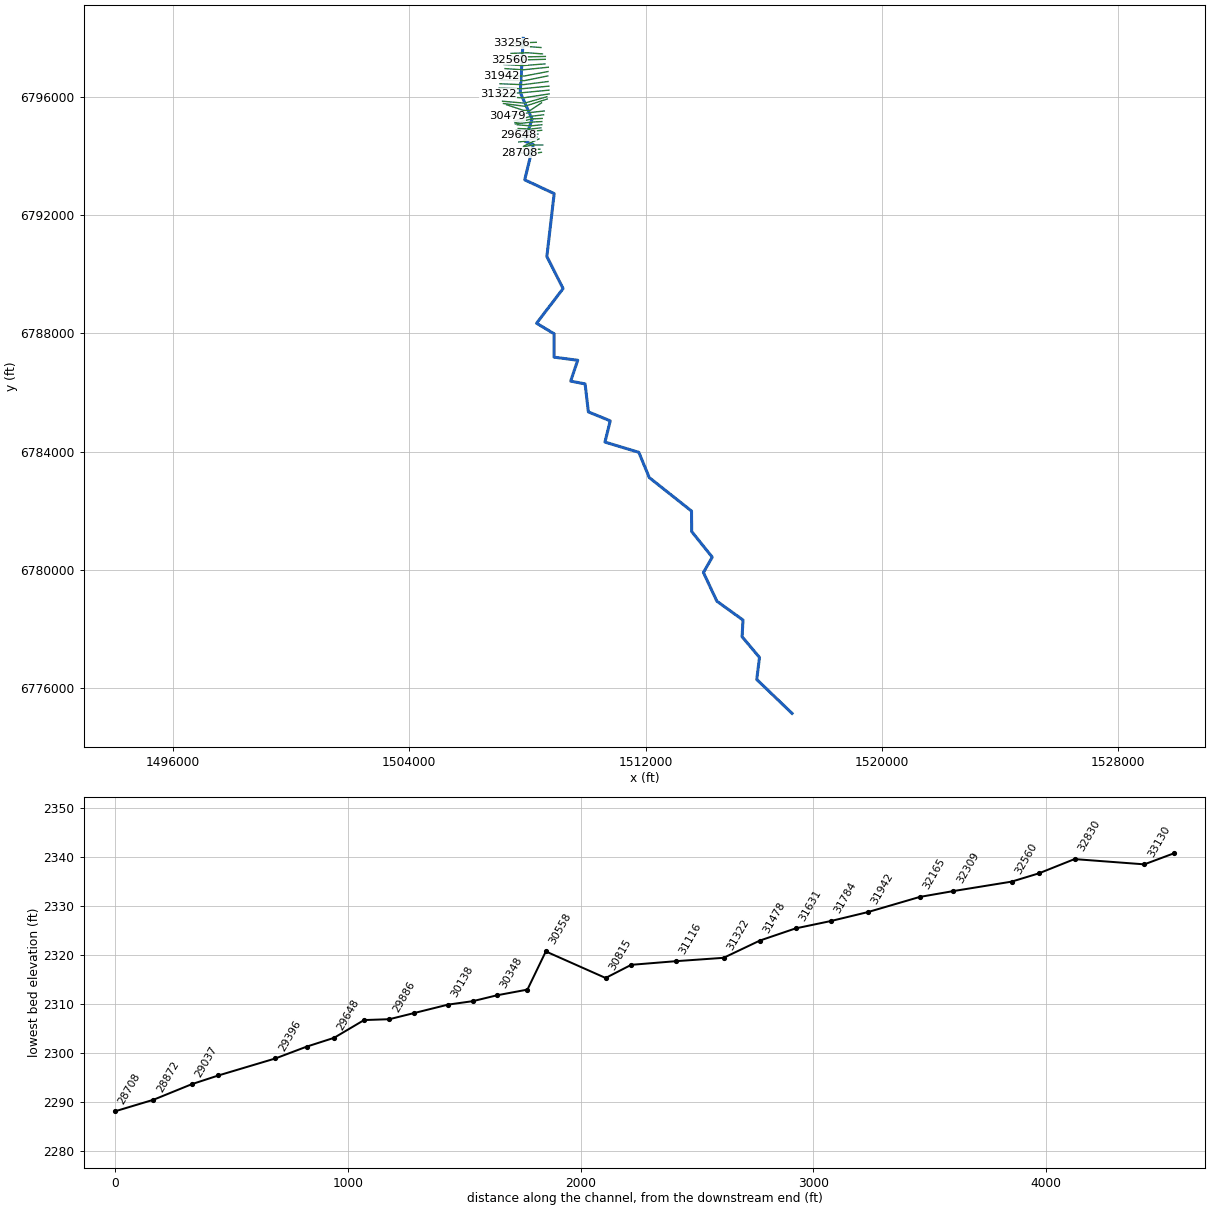
--- Cedar Creek 2.prj (project) ---

Proj Title=Cedar Creek 2 Base Level Engineering
Current Plan=p01
Default Exp/Contr=0.3,0.1
English Units
Geom File=g01
Flow File=f01
Plan File=p01
Y Axis Title=Elevation
X Axis Title(PF)=Main Channel Distance
X Axis Title(XS)=Station
BEGIN DESCRIPTION:
Cedar Creek 2
END DESCRIPTION:
DSS Export Rating Curves= 0
DSS Export Rating Curve Sorted= 0
DSS Export Volume Flow Curves= 0
DXF OffsetX= 0
DXF OffsetY= 0
DXF ScaleX= 1
DXF ScaleY= 10

--- Cedar Creek 2.p01 (plan) ---

Plan Title=Multiple Run
Program Version=4.10
Short Identifier=Multiple
Geom File=g01
Flow File=f01
Subcritical Flow
K Sum by GR= 0
Std Step Tol= 0.01
Critical Tol= 0.01
Num of Std Step Trials= 20
Max Error Tol= 0.3
Flow Tol Ratio= 0.001
Split Flow NTrial= 30
Split Flow Tol= 0.02
Split Flow Ratio= 0.02
Log Output Level= 0
Friction Slope Method= 1
Unsteady Friction Slope Method= 2
Unsteady Bridges Friction Slope Method= 1
Parabolic Critical Depth
Global Vel Dist= 1 , 1 , 1
Global Log Level= 0
CheckData=True
Encroach Param=-1 ,0,0, 0
BEGIN DESCRIPTION:
Multiple Run
END DESCRIPTION:
Computation Interval=1HOUR
Output Interval=1HOUR
Run HTab= 0
Run UNet= 0
Run PostProcess= 0
Run WQNet= 0
UNET Theta= 1
UNET Theta Warmup= 1
UNET ZTol= 0.02
UNET ZSATol= 0.05
UNET MxIter= 20
UNET MaxInSteps= 0
UNET DtIC= 0
UNET DtMin= 0
UNET MaxCRTS= 20
UNET WFStab= 2
UNET SFStab= 1
UNET WFX= 1
UNET SFX= 1
UNET DSS MLevel= 4
UNET DZMax Abort= 100
UNET Convert EG Bridges= 0
UNET Use Existing IB Tables=-1
UNET Froude Reduction=False
UNET Froude Limit= 1
UNET Froude Power= 10
UNET Time Slicing=0,0, 5
UNET Junction Losses=0
Instantaneous Interval=1HOUR
Write IC File= 0
Write IC File at Sim End=0
Echo Input=False
Echo Parameters=False
Echo Output=False
Write Detailed= 0
WQ AD Non Conservative
WQ ULTIMATE=-1
WQ Max Comp Step=1HOUR
WQ Output Interval=15MIN
WQ Output Selected Increments= 0
WQ Output face flow=0
WQ Output face velocity=0
WQ Output face area=0
WQ Output face dispersion=0
WQ Output cell volume=0
WQ Output cell surface area=0
WQ Output cell continuity=0
WQ Output cumulative cell continuity=0
WQ Output face conc=0
WQ Output face dconc_dx=0
WQ Output face courant=0
WQ Output face peclet=0
WQ Output face adv mass=0
WQ Output face disp mass=0
WQ Output cell mass=0
WQ Output cell source sink temp=0
WQ Output cell source sink nsm=0
WQ Output MaxMinRange=-1
WQ Daily Max Min Mean=-1
WQ Daily Range=0
WQ Daily Time=0
WQ Create Restart=0
WQ Fixed Restart=0
WQ System Summary=0
WQ Use Fixed Temperature=0
Sorting and Armoring Iterations= 10
XS Update Threshold= 0.02
Hydraulics Update Threshold= 0.02
Energy Slope Method= 1
Volume Change Method= 0
XS Weighting Method= 0
Number of US Weighted Cross Sections= 1
Number of DS Weighted Cross Sections= 1
Upstream XS Weight=0.25
Main XS Weight=0.5
Downstream XS Weight=0.25
Number of DS XS's Weighted with US Boundary= 1
Upstream Boundary Weight= 1
Weight of XSs Associated with US Boundary= 0
Number of US XS's Weighted with DS Boundary= 1
Downstream Boundary Weight= 0.5
Weight of XSs Associated with DS Boundary= 0.5
Sediment Output Level= 4
Mass or Volume Output= 0
Output Increment Type= 1
Profile and TS Output Increment= 10
XS Output Flag= 0
XS Output Increment= 10
Disregard all LS=0
Disregard all Conn=0
Disregard all Breaches=0
Disregard all Pumps=0

--- Cedar Creek 2.f01 (steady flow) ---

Flow Title=Multiple
Number of Profiles=7
Profile Names=10-year,25-year,50-year,1pct_min,100-year,1pct_plu,500-year
River Rch & RM= Cedar Creek 2,Reach-1,33256
     228     318     392     300     481     662     734
River Rch & RM= Cedar Creek 2,Reach-1,27428
     594     871    1110     879    1410    1940    2290
River Rch & RM= Cedar Creek 2,Reach-1,26982
     810    1200    1550    1240    1980    2730    3280
River Rch & RM= Cedar Creek 2,Reach-1,20767
     916    1360    1750    1390    2220    3060    3660
River Rch & RM= Cedar Creek 2,Reach-1,9775
    1380    2080    2700    2170    3480    4780    5830
Boundary for River Rch & Prof#=Cedar Creek 2,Reach-1,1
Up Type=0
Dn Type=3
Dn Slope=0.005
Boundary for River Rch & Prof#=Cedar Creek 2,Reach-1,2
Up Type=0
Dn Type=3
Dn Slope=0.005
Boundary for River Rch & Prof#=Cedar Creek 2,Reach-1,3
Up Type=0
Dn Type=3
Dn Slope=0.005
Boundary for River Rch & Prof#=Cedar Creek 2,Reach-1,4
Up Type=0
Dn Type=3
Dn Slope=0.005
Boundary for River Rch & Prof#=Cedar Creek 2,Reach-1,5
Up Type=0
Dn Type=3
Dn Slope=0.005
Boundary for River Rch & Prof#=Cedar Creek 2,Reach-1,6
Up Type=0
Dn Type=3
Dn Slope=0.005
Boundary for River Rch & Prof#=Cedar Creek 2,Reach-1,7
Up Type=0
Dn Type=3
Dn Slope=0.005

--- Cedar Creek 2.g01 (geometry) ---

Geom Title=Existing Conditions
Program Version=4.10

River Reach=Cedar Creek 2   ,Reach-1
Reach XY= 30
        1507855.        6797988.      1507754.95      6796153.34
      1508155.43      6795253.18      1507904.77      6794508.01
      1508197.69      6794388.11      1507905.54      6793198.64
      1508902.96      6792732.15      1508655.38      6790603.15
      1509205.11      6789517.91      1508307.04      6788343.85
      1508902.06      6787986.01      1508898.83      6787195.86
      1509699.65       6787090.7      1509462.77      6786384.56
      1509949.61      6786290.69      1510060.16      6785343.41
      1510799.63      6785040.38      1510621.43      6784321.16
      1511768.38      6783974.47      1512121.45      6783120.86
      1513551.95      6781986.38      1513557.18      6781293.45
       1514253.5      6780426.12      1513955.23      6779906.57
      1514410.39      6778935.32      1515294.05      6778298.38
      1515264.41      6777731.34      1515853.18      6777031.88
        1515760.      6776285.43        1516955.        6775138.

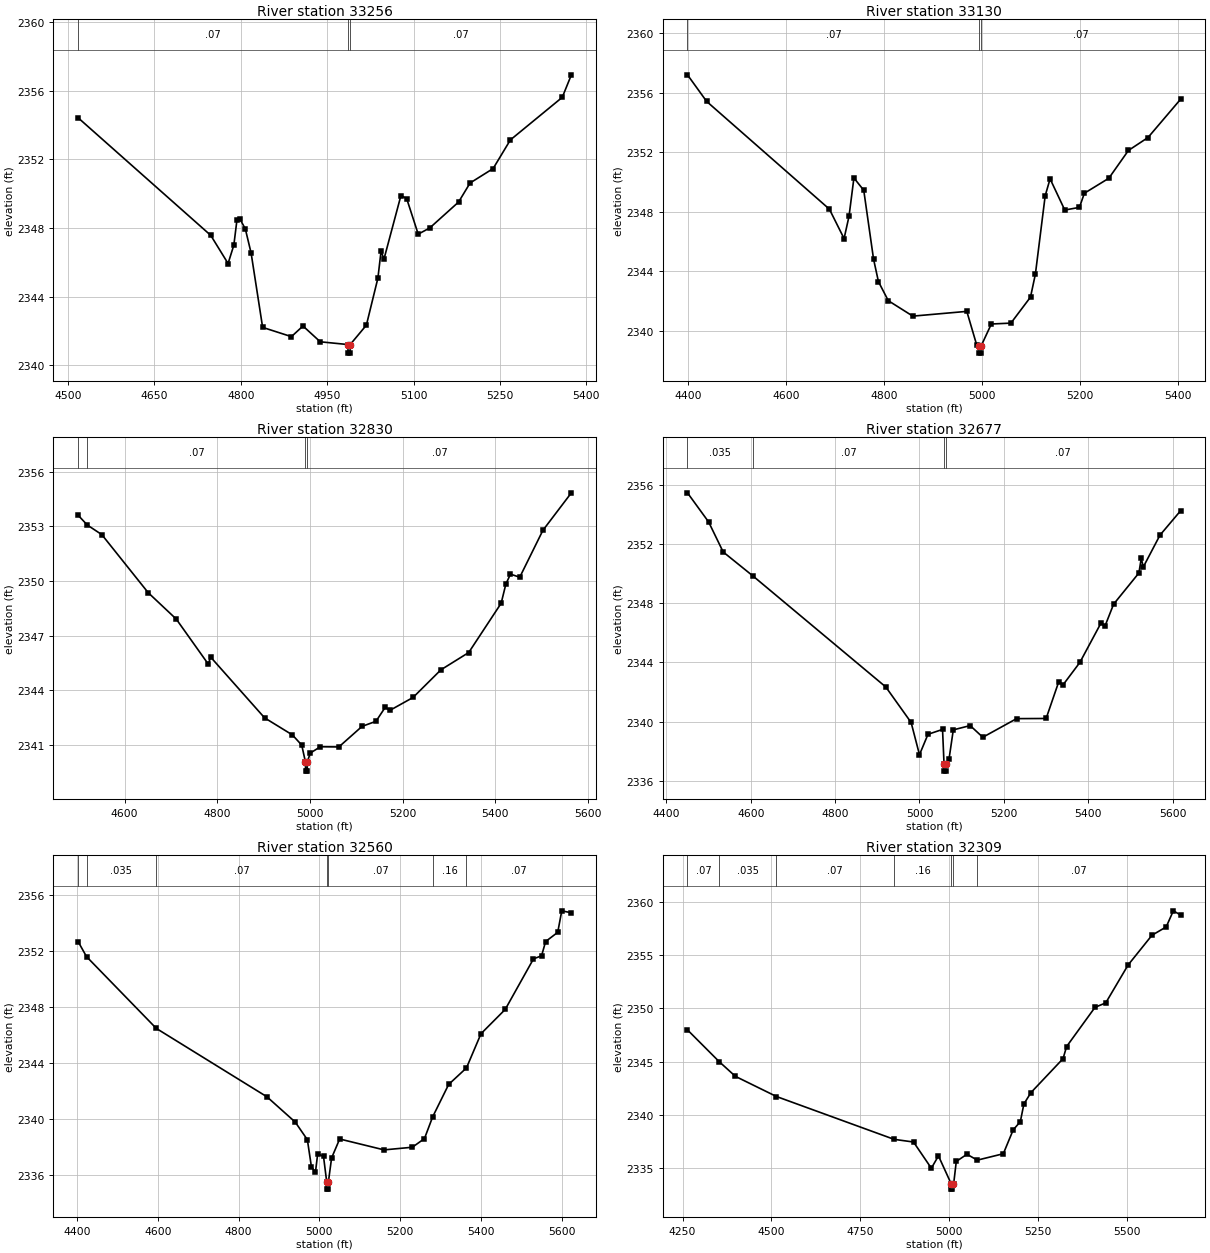
Type RM Length L Ch R = 1 ,33256   ,126,126,126
BEGIN DESCRIPTION:
7
END DESCRIPTION:
XS GIS Cut Line= 3
      1508295.25      6797854.14      1507813.04       6797834.7
      1507439.22      6797820.32
#Sta/Elev= 30
  4517.4 2354.42  4747.8 2347.57  4777.9 2345.93  4787.9    2347  4793.4 2348.49
  4798.4 2348.53  4807.9 2347.94  4817.9 2346.54  4837.9 2342.21  4887.9 2341.67
    4908 2342.29    4938 2341.37    4986 2341.21  4986.3 2340.71  4989.8 2340.71
    4990 2341.21  5018.1 2342.34  5038.1 2345.08  5043.6 2346.66  5048.6 2346.18
  5078.1 2349.89  5088.1 2349.71  5108.1 2347.64  5128.1    2348  5178.2 2349.51
  5198.2 2350.62  5238.2 2351.46  5268.2 2353.13  5358.3 2355.61  5374.1 2356.92
#Mann= 3 ,-1 , 0
  4517.4     .07       0    4986     .07       0    4990     .07       0
Bank Sta=4986,4990
XS Rating Curve= 0 ,0
Exp/Cntr=0.3,0.1

Type RM Length L Ch R = 1 ,33130   ,300,300,300
BEGIN DESCRIPTION:
613
END DESCRIPTION:
XS GIS Cut Line= 3
      1508454.08      6797677.06      1507855.14      6797721.33
      1507448.11      6797721.33
#Sta/Elev= 30
    4399 2357.21  4438.2 2355.42  4688.9 2348.17  4718.9 2346.19    4729 2347.69
    4739 2350.27  4759.1 2349.44  4779.1 2344.81  4789.1 2343.29  4809.2 2342.01
  4859.3 2340.97  4969.6 2341.29  4989.7 2339.04  4995.1 2338.98  4995.4 2338.48
  4998.9 2338.48  4999.1 2338.98  5019.7 2340.44  5059.7  2340.5  5099.7 2342.25
  5109.7  2343.8  5129.7 2349.07  5139.7 2350.21  5169.7 2348.11  5199.7 2348.29
  5209.7 2349.24  5259.7 2350.25  5299.7 2352.12  5339.7 2352.99  5406.6 2355.58
#Mann= 3 ,-1 , 0
    4399     .07       0  4995.1     .07       0  4999.1     .07       0
Bank Sta=4995.1,4999.1
XS Rating Curve= 0 ,0
Exp/Cntr=0.3,0.1

Type RM Length L Ch R = 1 ,32830   ,153,153,153
BEGIN DESCRIPTION:
612
END DESCRIPTION:
XS GIS Cut Line= 3
      1508506.15      6797460.92      1508003.58      6797499.98
      1507443.65      6797479.14
#Sta/Elev= 30
  4499.5 2353.62  4519.4 2353.08  4550.8 2352.55  4650.8 2349.36  4711.3 2347.91
  4780.5 2345.43  4785.5 2345.82  4901.9 2342.48    4962 2341.54  4982.1 2340.98
  4990.1 2340.05  4990.4 2339.55  4993.9 2339.55  4994.1 2340.05  5000.4 2340.54
  5022.2 2340.89  5062.2 2340.88  5112.2 2342.01  5142.3 2342.29  5162.3 2343.06
  5172.3 2342.89  5222.3  2343.6  5282.4 2345.12  5342.4 2346.07  5412.4 2348.78
  5422.5 2349.83  5432.5 2350.38  5452.5 2350.21  5502.5 2352.79  5563.9 2354.85
#Mann= 4 ,-1 , 0
  4499.5    .035       0  4519.4     .07       0  4990.1     .07       0
  4994.1     .07       0
Bank Sta=4990.1,4994.1
XS Rating Curve= 0 ,0
Exp/Cntr=0.3,0.1

Type RM Length L Ch R = 1 ,32677   ,117,117,117
BEGIN DESCRIPTION:
611
END DESCRIPTION:
XS GIS Cut Line= 3
      1508605.15      6797374.98      1508050.46      6797361.95
      1507435.85      6797374.98
#Sta/Elev= 30
  4449.9 2355.47  4500.1  2353.5  4534.6 2351.47  4605.9 2349.83  4920.2 2342.34
  4980.2 2339.94    5000 2337.76  5020.2 2339.14  5054.7 2339.47  5058.2 2337.15
  5058.5 2336.65    5062 2336.65  5062.2 2337.15  5070.2 2337.49  5080.2 2339.44
  5120.2 2339.73  5150.2 2338.94  5230.3  2340.2  5300.3 2340.21  5330.3  2342.7
  5340.3 2342.48  5380.3    2344  5430.3 2346.66  5440.3 2346.49  5460.3 2347.94
  5520.3 2350.05  5525.8 2351.03  5530.8 2350.46  5570.3 2352.61  5619.5 2354.27
#Mann= 4 ,-1 , 0
  4449.9    .035       0  4605.9     .07       0  5058.2     .07       0
  5062.2     .07       0
Bank Sta=5058.2,5062.2
XS Rating Curve= 0 ,0
Exp/Cntr=0.3,0.1

Type RM Length L Ch R = 1 ,32560   ,251,251,251
BEGIN DESCRIPTION:
610
END DESCRIPTION:
XS GIS Cut Line= 3
      1508602.53      6797278.62      1508008.79      6797260.39
      1507381.22        6797263.
#Sta/Elev= 30
  4402.3 2352.69  4423.2 2351.61    4596 2346.47  4870.1 2341.57  4940.1 2339.76
  4970.1  2338.5  4980.1 2336.57  4990.1 2336.16  4995.7  2337.5  5010.1  2337.3
  5018.1 2335.46  5018.4 2334.96  5021.9 2334.96  5022.1 2335.46  5030.1 2337.19
  5050.1 2338.55  5160.1 2337.77  5230.1 2337.96  5260.1 2338.58  5280.3 2340.13
  5320.1 2342.46  5364.1 2343.64  5400.1 2346.09  5460.1 2347.83  5530.1 2351.45
  5550.1 2351.67  5560.1 2352.69  5590.1 2353.35  5600.1 2354.89  5623.9 2354.75
#Mann= 7 ,-1 , 0
  4402.3     .07       0  4423.2    .035       0    4596     .07       0
  5018.1     .07       0  5022.1     .07       0  5280.3     .16       0
  5364.1     .07       0
Bank Sta=5018.1,5022.1
XS Rating Curve= 0 ,0
Exp/Cntr=0.3,0.1

Type RM Length L Ch R = 1 ,32309   ,144,144,144
BEGIN DESCRIPTION:
609
END DESCRIPTION:
XS GIS Cut Line= 3
      1508589.56      6797122.37      1507844.73      6797065.08
      1507204.09      6797101.54
#Sta/Elev= 30
  4263.9 2347.97  4353.2 2344.99  4398.9 2343.61  4514.4 2341.72  4845.7  2337.7
  4900.3 2337.45  4950.5 2334.99  4970.5 2336.15  5006.3 2333.53  5006.5 2333.03
    5010 2333.03  5010.3 2333.53  5013.3 2333.53  5020.7 2335.63  5050.7  2336.3
  5079.9 2335.75  5153.1 2336.35  5180.9 2338.59    5201 2339.36    5211 2341.02
    5231 2342.09  5321.2 2345.27  5331.3 2346.41  5411.3 2350.09  5441.4  2350.5
  5504.4 2354.06  5571.6 2356.85  5611.6 2357.63  5631.7 2359.14  5652.6 2358.74
#Mann= 7 ,-1 , 0
  4263.9     .07       0  4353.2    .035       0  4514.4     .07       0
  4845.7     .16       0  5006.3     .07       0  5010.3     .16       0
  5079.9     .07       0
Bank Sta=5006.3,5010.3
XS Rating Curve= 0 ,0
Exp/Cntr=0.3,0.1

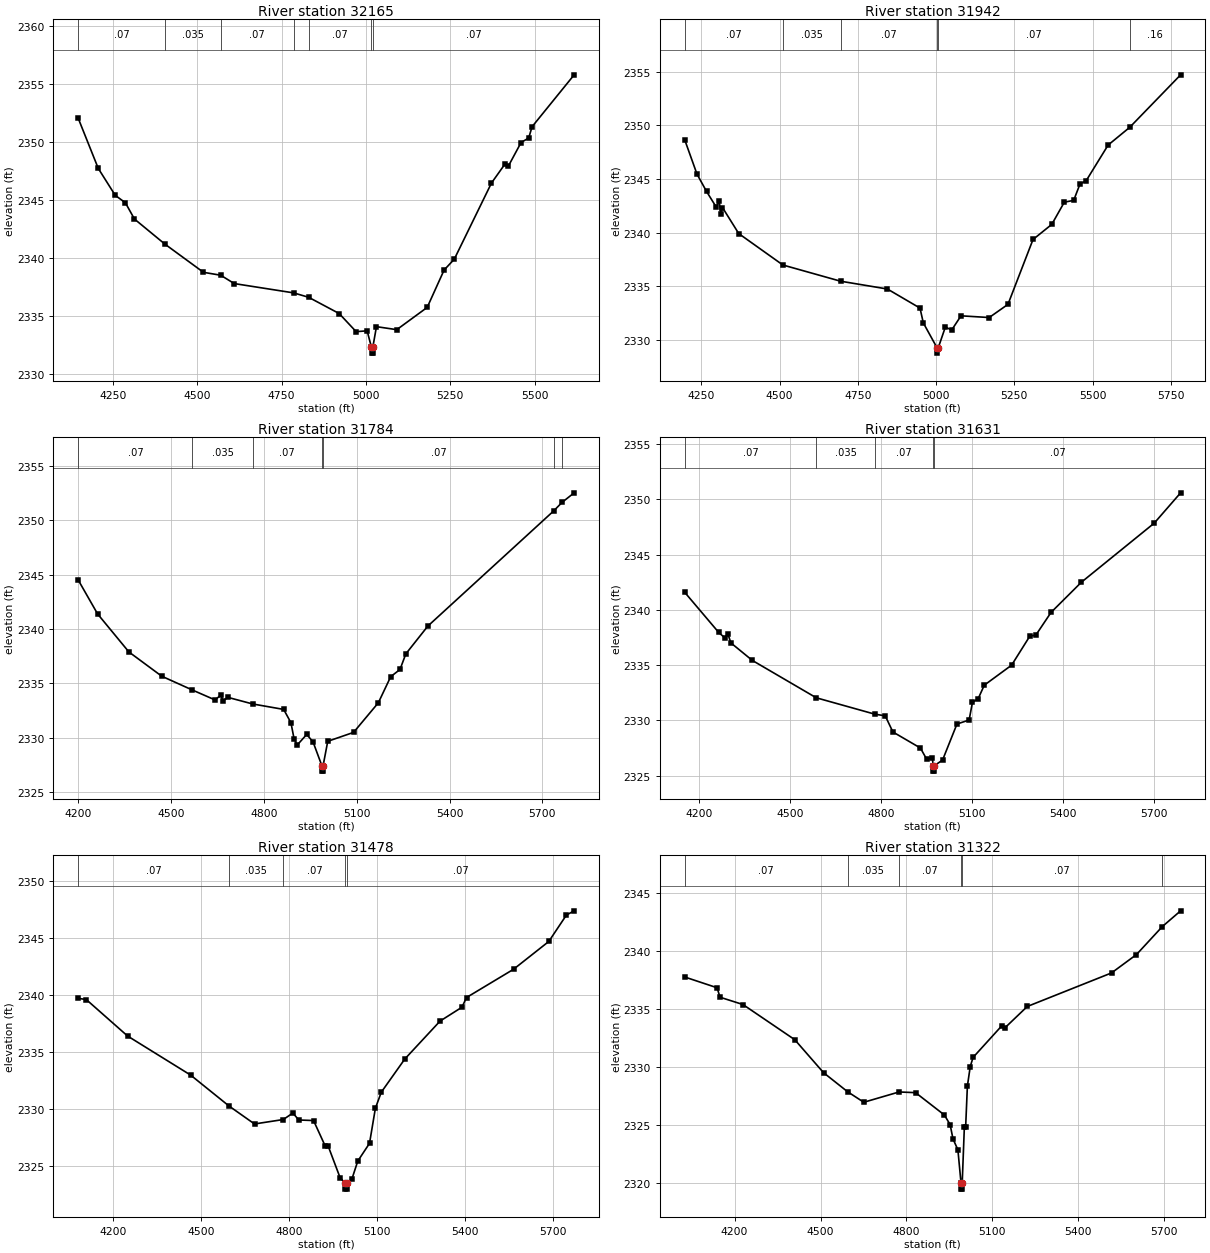
Type RM Length L Ch R = 1 ,32165   ,223,223,223
BEGIN DESCRIPTION:
608
END DESCRIPTION:
XS GIS Cut Line= 3
      1508704.08      6797010.39      1507852.54      6796921.85
      1507240.59      6796963.51
#Sta/Elev= 30
  4147.3 2352.07  4206.7 2347.75    4257 2345.43  4287.1 2344.79  4313.9 2343.39
  4403.7 2341.24  4518.4  2338.8  4569.5 2338.55  4609.7 2337.83  4785.4 2337.03
  4830.1 2336.65  4920.5 2335.25  4970.8 2333.69  5003.4 2333.76  5016.2 2332.34
  5016.4 2331.84  5019.9 2331.84  5020.2 2332.34    5031 2334.12  5091.2 2333.86
  5181.4 2335.78  5231.5    2339  5261.6 2339.93  5371.8 2346.49  5411.9 2348.13
  5421.9 2347.95  5459.5 2349.98  5482.1 2350.37  5492.1 2351.34  5616.8 2355.81
#Mann= 7 ,-1 , 0
  4147.3     .07       0  4403.7    .035       0  4569.5     .07       0
  4785.4     .16       0  4830.1     .07       0  5016.2     .07       0
  5020.2     .07       0
Bank Sta=5016.2,5020.2
XS Rating Curve= 0 ,0
Exp/Cntr=0.3,0.1

Type RM Length L Ch R = 1 ,31942   ,158,158,158
BEGIN DESCRIPTION:
607
END DESCRIPTION:
XS GIS Cut Line= 3
      1508693.64      6796864.55      1507899.41      6796713.52
      1507123.38      6796713.52
#Sta/Elev= 30
    4197 2348.66  4236.3 2345.45  4266.9 2343.83  4297.4 2342.39  4307.4 2342.91
  4312.5 2341.69  4317.8 2342.33  4369.8  2339.9  4510.8 2336.97  4694.9 2335.46
  4844.8 2334.73  4948.9 2332.95  4959.4 2331.57  5003.2 2329.25  5003.4 2328.75
  5007.2 2329.25  5029.9 2331.19  5049.9  2330.9  5079.9 2332.23  5169.9 2332.07
  5229.9  2333.3  5309.9 2339.35  5369.9 2340.76  5409.9 2342.83  5439.9    2343
  5459.9 2344.52  5479.9 2344.84  5549.9 2348.16  5618.8 2349.81  5781.5 2354.71
#Mann= 6 ,-1 , 0
    4197     .07       0  4510.8    .035       0  4694.9     .07       0
  5003.2     .07       0  5007.2     .07       0  5618.8     .16       0
Bank Sta=5003.2,5007.2
XS Rating Curve= 0 ,0
Exp/Cntr=0.3,0.1

Type RM Length L Ch R = 1 ,31784   ,153,153,153
BEGIN DESCRIPTION:
606
END DESCRIPTION:
XS GIS Cut Line= 3
      1508688.52      6796716.13      1507896.81      6796554.66
      1507102.54       6796580.7
#Sta/Elev= 30
  4199.9  2344.5  4262.6 2341.38  4363.7 2337.89  4469.9 2335.66    4569 2334.39
  4642.3 2333.48  4661.8 2333.96  4666.9 2333.36  4683.2 2333.72  4763.8 2333.11
  4863.9 2332.61  4887.3 2331.39  4897.5 2329.91  4907.7 2329.34  4938.3 2330.31
  4958.7 2329.63  4987.3 2327.44  4987.6 2326.94  4991.1 2326.94  4991.3 2327.44
  5006.3 2329.68  5089.8  2330.5  5169.8 2333.22  5209.8 2335.62  5239.8 2336.28
  5258.6 2337.71  5329.9 2340.27  5736.9 2350.86  5763.4 2351.63  5802.6 2352.51
#Mann= 7 ,-1 , 0
  4199.9     .07       0    4569    .035       0  4763.8     .07       0
  4987.3     .07       0  4991.3     .07       0  5736.9     .16       0
  5763.4     .07       0
Bank Sta=4987.3,4991.3
XS Rating Curve= 0 ,0
Exp/Cntr=0.3,0.1

Type RM Length L Ch R = 1 ,31631   ,153,153,153
BEGIN DESCRIPTION:
605
END DESCRIPTION:
XS GIS Cut Line= 3
      1508696.28      6796526.02      1507852.54      6796419.25
      1507068.02      6796450.42
#Sta/Elev= 30
  4152.6 2341.59  4264.8 2337.96  4284.9 2337.47    4295 2337.82  4305.1 2337.01
  4375.6 2335.43  4586.6 2332.05  4779.6 2330.57    4814 2330.42  4839.3 2328.96
    4930 2327.51  4950.2 2326.52  4969.2 2326.62  4972.3 2325.92  4972.5 2325.42
    4976 2325.42  4976.3 2325.92  5003.1 2326.42  5050.6 2329.68  5090.7 2330.04
  5101.6 2331.63  5120.7 2331.98  5140.7 2333.19  5230.8    2335  5290.8 2337.62
  5310.8 2337.72  5360.9 2339.77    5461  2342.5  5701.2 2347.84  5788.2 2350.58
#Mann= 5 ,-1 , 0
  4152.6     .07       0  4586.6    .035       0  4779.6     .07       0
  4972.3     .07       0  4976.3     .07       0
Bank Sta=4972.3,4976.3
XS Rating Curve= 0 ,0
Exp/Cntr=0.3,0.1

Type RM Length L Ch R = 1 ,31478   ,156,156,156
BEGIN DESCRIPTION:
604
END DESCRIPTION:
XS GIS Cut Line= 3
      1508722.32      6796369.77      1507808.27      6796281.23
      1507038.76      6796304.62
#Sta/Elev= 30
  4082.7  2339.7  4110.2 2339.59  4250.8 2336.39  4465.4 2332.96  4595.9 2330.25
  4682.8 2328.67  4780.8 2329.06  4813.4 2329.63  4833.5 2329.02  4883.8 2328.97
  4923.9 2326.71    4934  2326.7  4974.2 2323.95  4992.3 2323.45  4992.5 2322.95
    4996 2322.95  4996.3 2323.45  5014.3 2323.83  5034.3 2325.41  5074.3 2326.97
  5094.3 2330.05  5114.4 2331.46  5194.4 2334.37  5314.4  2337.7    5389 2338.92
  5404.5 2339.77  5564.6 2342.25  5684.6 2344.69  5744.6 2347.01  5770.9 2347.38
#Mann= 5 ,-1 , 0
  4082.7     .07       0  4595.9    .035       0  4780.8     .07       0
  4992.3     .07       0  4996.3     .07       0
Bank Sta=4992.3,4996.3
XS Rating Curve= 0 ,0
Exp/Cntr=0.3,0.1

Type RM Length L Ch R = 1 ,31322   ,206,206,206
BEGIN DESCRIPTION:
603
END DESCRIPTION:
XS GIS Cut Line= 3
       1508727.5      6796234.35      1507750.98       6796140.6
      1507000.95      6796114.56
#Sta/Elev= 30
  4025.8 2337.77  4138.8 2336.84  4149.2 2336.02  4229.2 2335.39  4410.1 2332.35
  4510.5  2329.5  4594.6 2327.85  4651.2 2326.94  4774.3 2327.83    4832 2327.77
  4932.5 2325.84  4952.5 2325.01  4962.6 2323.77  4979.7 2322.83  4990.7 2319.93
    4991 2319.43  4994.5 2319.43  4994.7 2319.93  5002.3 2324.83  5006.8 2324.83
  5012.8 2328.33  5022.8 2330.03  5032.8 2330.82  5132.9 2333.55  5142.9 2333.35
  5221.9 2335.22    5516 2338.12  5603.2 2339.71  5693.5 2342.13  5757.3 2343.49
#Mann= 6 ,-1 , 0
  4025.8     .07       0  4594.6    .035       0  4774.3     .07       0
  4990.7     .07       0  4994.7     .07       0  5693.5     .16       0
Bank Sta=4990.7,4994.7
XS Rating Curve= 0 ,0
Exp/Cntr=0.3,0.1

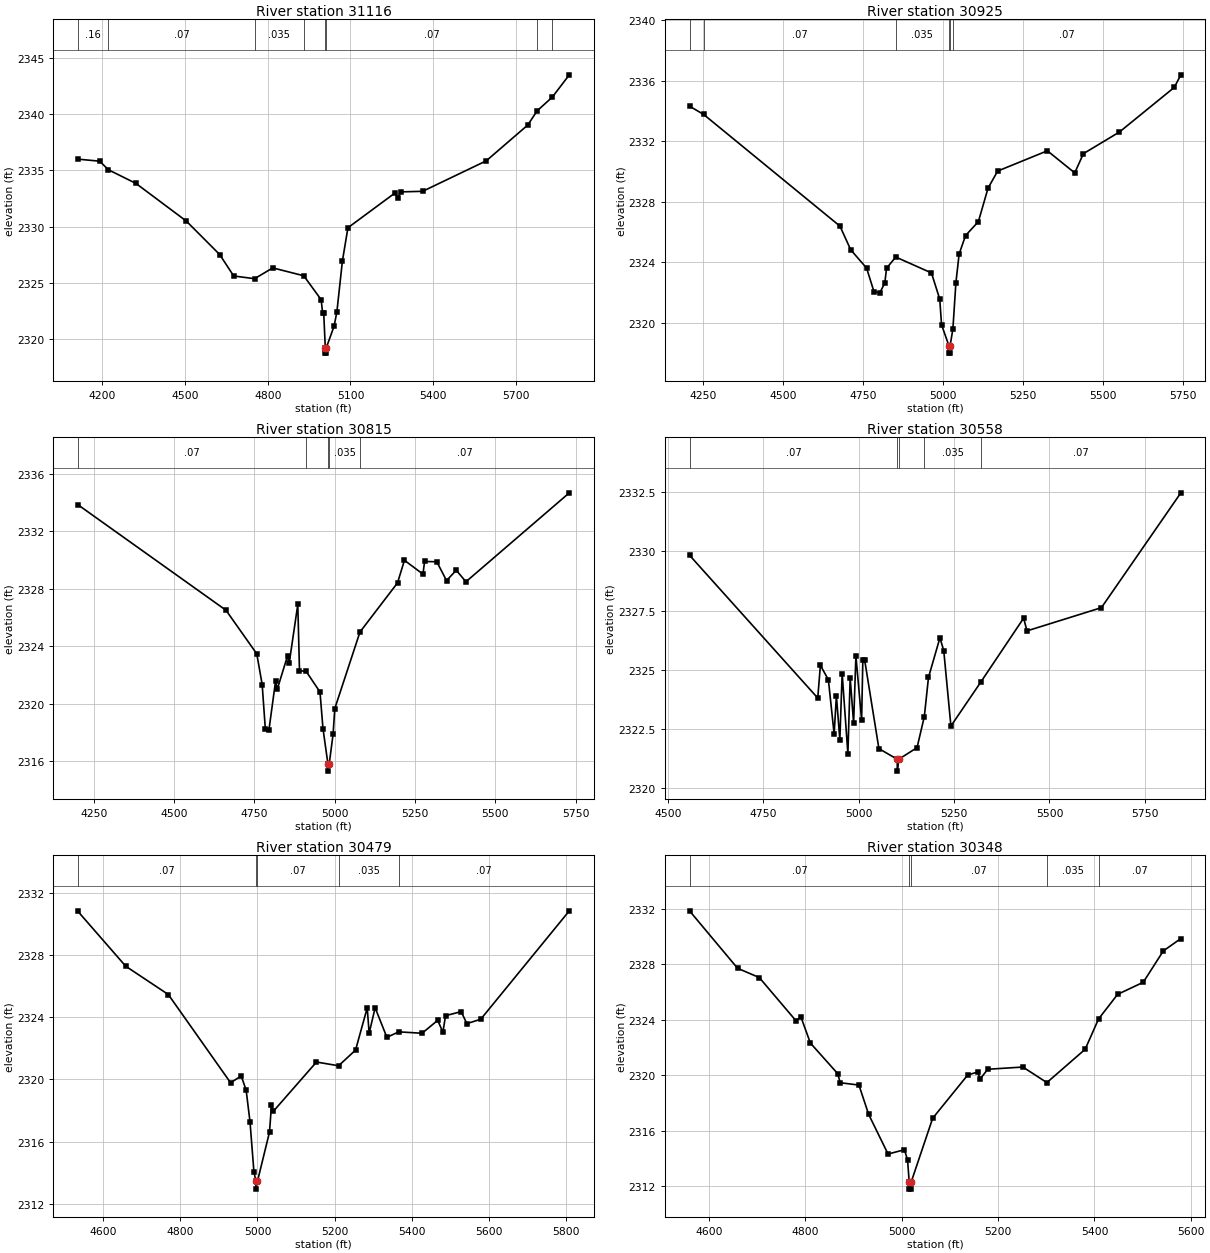
Type RM Length L Ch R = 1 ,31116   ,191,191,191
BEGIN DESCRIPTION:
602
END DESCRIPTION:
XS GIS Cut Line= 3
      1508732.79      6796106.75      1507852.54      6795971.33
      1506964.56      6796031.22
#Sta/Elev= 30
  4112.5 2335.99  4191.2 2335.81  4222.5 2335.05  4322.7 2333.83  4504.8 2330.49
  4626.3  2327.5  4676.8  2325.6  4752.4 2325.36  4818.5 2326.32  4930.7 2325.62
  4993.8 2323.49  4999.3 2322.27  5003.1 2322.27  5008.7 2319.24  5008.9 2318.74
  5012.4 2318.74  5012.7 2319.24  5040.7 2321.14  5050.8 2322.42  5070.8 2326.94
  5090.8 2329.89  5261.2 2332.98  5271.3  2332.5  5281.3 2333.08  5361.5 2333.13
    5592 2335.84  5742.3 2339.02  5776.6 2340.29  5831.5 2341.51  5893.1 2343.49
#Mann= 8 ,-1 , 0
  4112.5     .16       0  4222.5     .07       0  4752.4    .035       0
  4930.7     .07       0  5008.7     .07       0  5012.7     .07       0
  5776.6     .16       0  5831.5     .07       0
Bank Sta=5008.7,5012.7
XS Rating Curve= 0 ,0
Exp/Cntr=0.3,0.1

Type RM Length L Ch R = 1 ,30925   ,110,110,110
BEGIN DESCRIPTION:
601
END DESCRIPTION:
XS GIS Cut Line= 3
      1508657.24       6796010.4      1507899.41      6795794.25
      1507154.61      6795859.35
#Sta/Elev= 30
  4208.3 2334.32  4252.6 2333.77  4678.6 2326.39  4712.1 2324.83  4761.8 2323.62
    4785 2322.05  4803.4 2321.99  4818.8 2322.65  4824.2 2323.61  4852.9 2324.35
  4964.5  2323.3  4990.5 2321.56    4996 2319.88  5018.9  2318.5  5019.1    2318
  5022.6    2318  5022.9  2318.5  5031.5  2319.6  5040.9 2322.65    5051 2324.55
  5071.1 2325.77  5111.2 2326.69  5141.3  2328.9  5171.4 2330.03  5326.8 2331.37
  5412.3 2329.91  5439.4 2331.18    5552 2332.61  5723.5 2335.56    5744 2336.39
#Mann= 6 ,-1 , 0
  4208.3     .16       0  4252.6     .07       0  4852.9    .035       0
  5018.9    .035       0  5022.9    .035       0  5031.5     .07       0
Bank Sta=5018.9,5022.9
XS Rating Curve= 0 ,0
Exp/Cntr=0.3,0.1

Type RM Length L Ch R = 1 ,30815   ,257,257,257
BEGIN DESCRIPTION:
600
END DESCRIPTION:
XS GIS Cut Line= 3
      1508670.24      6795934.87      1507909.83      6795687.48
      1507185.91      6795781.22
#Sta/Elev= 30
  4200.5 2333.83  4661.3  2326.5  4757.1 2323.47  4773.9 2321.34  4783.7 2318.26
  4794.9 2318.17  4815.7 2321.59  4820.9 2321.01  4852.9 2323.33  4858.1 2322.83
  4884.8  2326.9  4890.1 2322.29  4910.6 2322.26  4953.9 2320.82  4963.2 2318.28
  4978.6 2315.82  4978.9 2315.32  4982.6 2315.82  4994.7 2317.89    5000 2319.67
  5078.4 2324.99  5195.2  2328.4  5216.8 2329.97  5274.5 2329.01  5279.5 2329.89
  5317.6 2329.87  5347.8 2328.56  5378.1 2329.28  5408.3 2328.48  5730.1 2334.66
#Mann= 5 ,-1 , 0
  4200.5     .07       0  4910.6    .035       0  4978.6    .035       0
  4982.6    .035       0  5078.4     .07       0
Bank Sta=4978.6,4982.6
XS Rating Curve= 0 ,0
Exp/Cntr=0.3,0.1

Type RM Length L Ch R = 1 ,30558   ,79,79,79
BEGIN DESCRIPTION:
595
END DESCRIPTION:
XS GIS Cut Line= 4
      1508474.46       6795804.2      1508094.73      6795550.32
      1507862.52      6795550.32      1507293.94      6795739.13
#Sta/Elev= 30
  4556.3 2329.83  4892.5 2323.81  4899.4 2325.19  4920.4 2324.58  4935.4  2322.3
  4941.4  2323.9  4950.4 2322.05  4956.5 2324.84  4971.5 2321.46  4977.5 2324.67
  4986.5 2322.74  4992.5 2325.59  5007.5 2322.88  5010.7 2325.42  5015.4 2325.42
  5052.8 2321.68  5100.8 2321.23  5101.1 2320.73  5104.8 2321.23  5152.8 2321.72
  5171.9 2323.03  5182.8 2324.68  5212.8 2326.35  5222.8 2325.81  5241.6 2322.63
  5319.4 2324.47  5432.3 2327.18  5440.9 2326.64  5636.2 2327.62  5844.4 2332.46
#Mann= 5 ,-1 , 0
  4556.3     .07       0  5100.8     .07       0  5104.8     .07       0
  5171.9    .035       0  5319.4     .07       0
Bank Sta=5100.8,5104.8
XS Rating Curve= 0 ,0
Exp/Cntr=0.3,0.1

Type RM Length L Ch R = 1 ,30479   ,131,131,131
BEGIN DESCRIPTION:
596
END DESCRIPTION:
XS GIS Cut Line= 3
      1508567.85      6795528.62      1508105.58      6795478.71
      1507308.52      6795350.92
#Sta/Elev= 30
  4535.3  2330.8  4658.9 2327.28  4769.2 2325.46  4930.4 2319.79  4957.9 2320.22
  4970.7 2319.32  4980.7 2317.28  4990.8 2314.08    4996 2313.45  4996.3 2312.95
    5000 2313.45  5031.2 2316.62  5036.3 2318.35  5041.4 2317.96  5152.8 2321.12
  5210.1 2320.88    5254 2321.89  5284.2  2324.6  5289.2 2322.97  5304.7 2324.61
  5335.1 2322.71    5366 2323.06  5426.2 2322.97  5466.7  2323.8  5480.2 2323.04
    5487  2324.1  5527.5 2324.36  5542.2 2323.59  5578.1 2323.87  5807.5 2330.84
#Mann= 5 ,-1 , 0
  4535.3     .07       0    4996     .07       0    5000     .07       0
  5210.1    .035       0    5366     .07       0
Bank Sta=4996,5000
XS Rating Curve= 0 ,0
Exp/Cntr=0.3,0.1

Type RM Length L Ch R = 1 ,30348   ,103,103,103
BEGIN DESCRIPTION:
597
END DESCRIPTION:
XS GIS Cut Line= 3
      1508543.97      6795400.59      1508101.24      6795346.33
        1507550.       6795187.9
#Sta/Elev= 30
  4559.6 2331.85  4659.3 2327.71  4704.4 2327.04  4780.2 2323.94  4790.9 2324.19
  4810.4 2322.32  4867.2 2320.11  4872.3 2319.46  4911.2 2319.29  4931.3 2317.18
  4971.6 2314.32  5005.6 2314.63  5012.1 2313.89  5015.5 2312.29  5015.8 2311.79
  5019.3 2311.79  5019.5 2312.29  5064.2  2316.9    5137 2320.02  5157.6 2320.23
  5162.8 2319.74  5178.6 2320.43  5251.4 2320.59  5301.2 2319.47  5380.6 2321.87
  5408.5 2324.06    5448 2325.83  5501.2  2326.7  5542.8 2328.96  5579.2 2329.85
#Mann= 5 ,-1 , 0
  4559.6     .07       0  5015.5     .07       0  5019.5     .07       0
  5301.2    .035       0  5408.5     .07       0
Bank Sta=5015.5,5019.5
XS Rating Curve= 0 ,0
Exp/Cntr=0.3,0.1

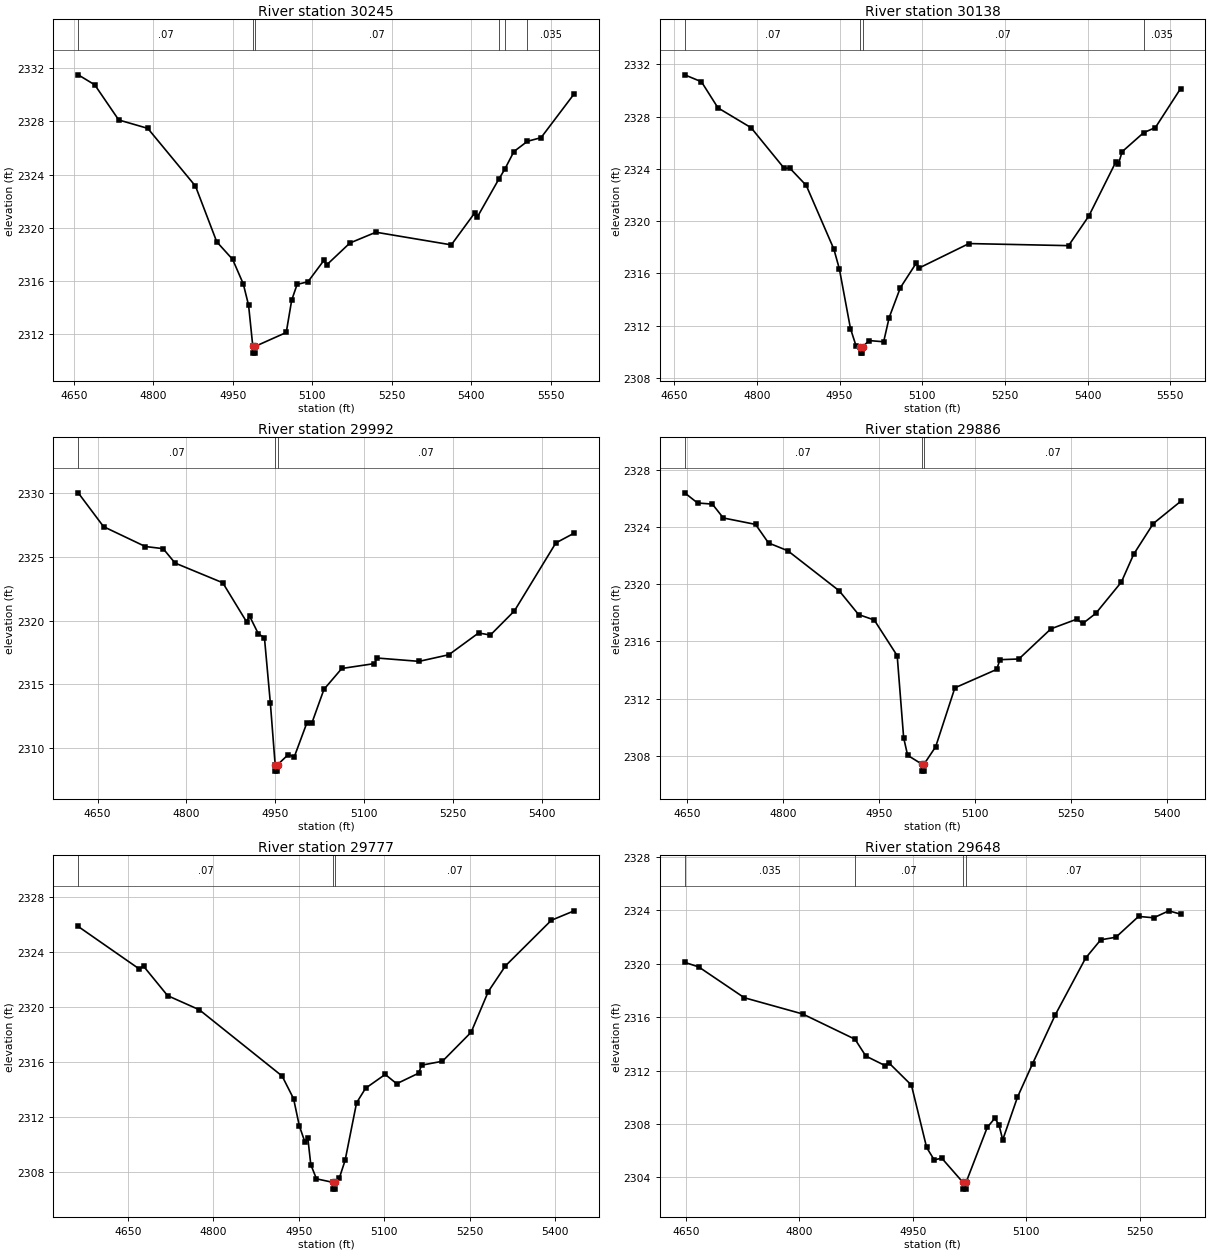
Type RM Length L Ch R = 1 ,30245   ,107,107,107
BEGIN DESCRIPTION:
598
END DESCRIPTION:
XS GIS Cut Line= 3
      1508496.16      6795276.88      1508153.32      6795259.52
      1507573.91      6795133.66
#Sta/Elev= 30
  4658.4  2331.5  4689.6 2330.75  4734.9 2328.11  4789.7 2327.48  4879.8 2323.14
  4919.9 2318.96  4949.9 2317.64    4970  2315.8    4980  2314.2    4988  2311.1
  4988.2  2310.6  4991.7  2310.6    4992  2311.1  5051.1 2312.15  5061.4 2314.58
  5071.6 2315.76  5092.1 2315.96  5122.1 2317.56  5127.3 2317.22  5171.3 2318.87
  5220.4 2319.68  5362.7 2318.73  5406.7 2321.12  5411.8 2320.82    5452 2323.64
  5463.5  2324.4  5480.9 2325.74  5506.5 2326.51  5532.1 2326.78  5594.6 2330.07
#Mann= 6 ,-1 , 0
  4658.4     .07       0    4988     .07       0    4992     .07       0
    5452    .035       0  5463.5     .07       0  5506.5    .035       0
Bank Sta=4988,4992
XS Rating Curve= 0 ,0
Exp/Cntr=0.3,0.1

Type RM Length L Ch R = 1 ,30138   ,146,146,146
BEGIN DESCRIPTION:
599
END DESCRIPTION:
XS GIS Cut Line= 3
      1508485.35      6795170.55      1508153.32      6795153.19
       1507589.5       6795090.3
#Sta/Elev= 30
    4669  2331.2  4699.4 2330.67  4729.4 2328.67  4789.5 2327.15  4849.6 2324.04
  4859.6 2324.06  4889.6 2322.73  4939.7 2317.85  4949.7 2316.33  4969.8 2311.77
  4979.8 2310.46  4987.8 2310.39    4988 2309.89  4991.5 2309.89  4991.8 2310.39
    5004 2310.85    5030 2310.76    5040 2312.61  5060.2 2314.89  5089.3 2316.79
  5094.4 2316.41  5184.8 2318.28  5365.5 2318.12  5402.3 2320.39  5450.9  2324.5
  5455.9 2324.36  5462.6 2325.31  5501.7 2326.77    5523 2327.16  5568.8 2330.15
#Mann= 4 ,-1 , 0
    4669     .07       0  4987.8     .07       0  4991.8     .07       0
  5501.7    .035       0
Bank Sta=4987.8,4991.8
XS Rating Curve= 0 ,0
Exp/Cntr=0.3,0.1

Type RM Length L Ch R = 1 ,29992   ,106,106,106
BEGIN DESCRIPTION:
594
END DESCRIPTION:
XS GIS Cut Line= 3
      1508487.55      6795064.21      1508107.75      6795022.98
      1507654.16      6795062.04
#Sta/Elev= 30
  4617.2 2330.05    4660 2327.39  4730.4 2325.83  4760.6 2325.66  4780.7 2324.53
  4861.2 2322.98  4901.4 2319.91  4906.4 2320.37  4921.5 2318.95  4931.6 2318.67
  4941.6 2313.52  4949.7 2308.67    4950 2308.17  4953.5 2308.17  4953.7 2308.67
  4971.8 2309.47  4981.9 2309.28  5003.2 2311.96    5012 2311.99  5032.1  2314.6
  5062.2 2316.24  5116.7 2316.62  5122.4 2317.06  5192.7  2316.8  5242.9 2317.32
  5293.1 2319.03  5313.1 2318.87  5353.7 2320.77  5423.6 2326.11  5454.5 2326.88
#Mann= 3 ,-1 , 0
  4617.2     .07       0  4949.7     .07       0  4953.7     .07       0
Bank Sta=4949.7,4953.7
XS Rating Curve= 0 ,0
Exp/Cntr=0.3,0.1

Type RM Length L Ch R = 1 ,29886   ,109,109,109
BEGIN DESCRIPTION:
593
END DESCRIPTION:
XS GIS Cut Line= 3
        1508455.      6794957.88      1508107.75      6794916.64
      1507682.39      6794936.17
#Sta/Elev= 30
  4646.2  2326.4  4666.3 2325.69  4689.5 2325.61  4706.6 2324.64    4757 2324.19
  4777.3 2322.89  4807.3 2322.35  4887.9 2319.54  4918.1 2317.88  4942.6  2317.5
  4978.5    2315  4988.6 2309.26  4994.8 2308.03  5016.7 2307.42  5016.9 2306.92
  5020.4 2306.92  5020.7 2307.42  5038.7 2308.63  5068.7 2312.75  5134.1 2314.04
  5139.2 2314.72  5168.8 2314.77  5218.9 2316.88  5258.9 2317.55  5268.9 2317.26
    5289 2317.96    5329 2320.15  5348.3  2322.1    5379 2324.25  5421.7  2325.8
#Mann= 3 ,-1 , 0
  4646.2     .07       0  5016.7     .07       0  5020.7     .07       0
Bank Sta=5016.7,5020.7
XS Rating Curve= 0 ,0
Exp/Cntr=0.3,0.1

Type RM Length L Ch R = 1 ,29777   ,129,129,129
BEGIN DESCRIPTION:
592
END DESCRIPTION:
XS GIS Cut Line= 3
        1508481.      6794875.41      1508029.62      6794827.67
      1507615.09      6794871.07
#Sta/Elev= 30
  4562.8 2325.88  4669.4  2322.8  4677.6 2322.98  4719.7 2320.84  4775.4 2319.81
  4920.8 2314.98  4940.9 2313.33    4951 2311.35    4961 2310.15    4966 2310.44
  4971.1 2308.53  4981.1 2307.49  5009.3 2307.24  5009.5 2306.74    5013 2306.74
  5013.3 2307.24  5021.5 2307.58  5031.4 2308.84  5051.5 2313.03  5067.3 2314.09
  5101.8  2315.1  5121.9 2314.42  5160.5 2315.19  5165.5 2315.77  5202.3 2316.06
  5252.6 2318.17  5282.8 2321.14  5312.9 2323.01  5393.4 2326.33  5433.5 2327.02
#Mann= 3 ,-1 , 0
  4562.8     .07       0  5009.3     .07       0  5013.3     .07       0
Bank Sta=5009.3,5013.3
XS Rating Curve= 0 ,0
Exp/Cntr=0.3,0.1

Type RM Length L Ch R = 1 ,29648   ,118,118,118
BEGIN DESCRIPTION:
591
END DESCRIPTION:
XS GIS Cut Line= 3
      1508353.45      6794747.81      1508002.71      6794714.82
      1507699.42      6794706.15
#Sta/Elev= 30
  4648.5 2320.11    4667 2319.77  4727.3 2317.46  4804.6 2316.24  4873.7 2314.35
    4888 2313.09  4913.3 2312.38  4918.3 2312.59  4948.3 2310.91  4968.4 2306.24
  4978.4 2305.31  4988.4 2305.44  5016.5 2303.62  5016.8 2303.12  5020.3 2303.12
  5020.5 2303.62  5048.5 2307.74  5058.5 2308.43    5064 2307.95    5069 2306.81
  5088.5 2310.01  5108.5 2312.52  5138.6 2316.19  5178.6 2320.43  5198.6  2321.8
  5218.6 2321.99  5248.6 2323.55  5268.6 2323.45  5288.6 2323.97  5304.2 2323.72
#Mann= 4 ,-1 , 0
  4648.5    .035       0  4873.7     .07       0  5016.5     .07       0
  5020.5     .07       0
Bank Sta=5016.5,5020.5
XS Rating Curve= 0 ,0
Exp/Cntr=0.3,0.1

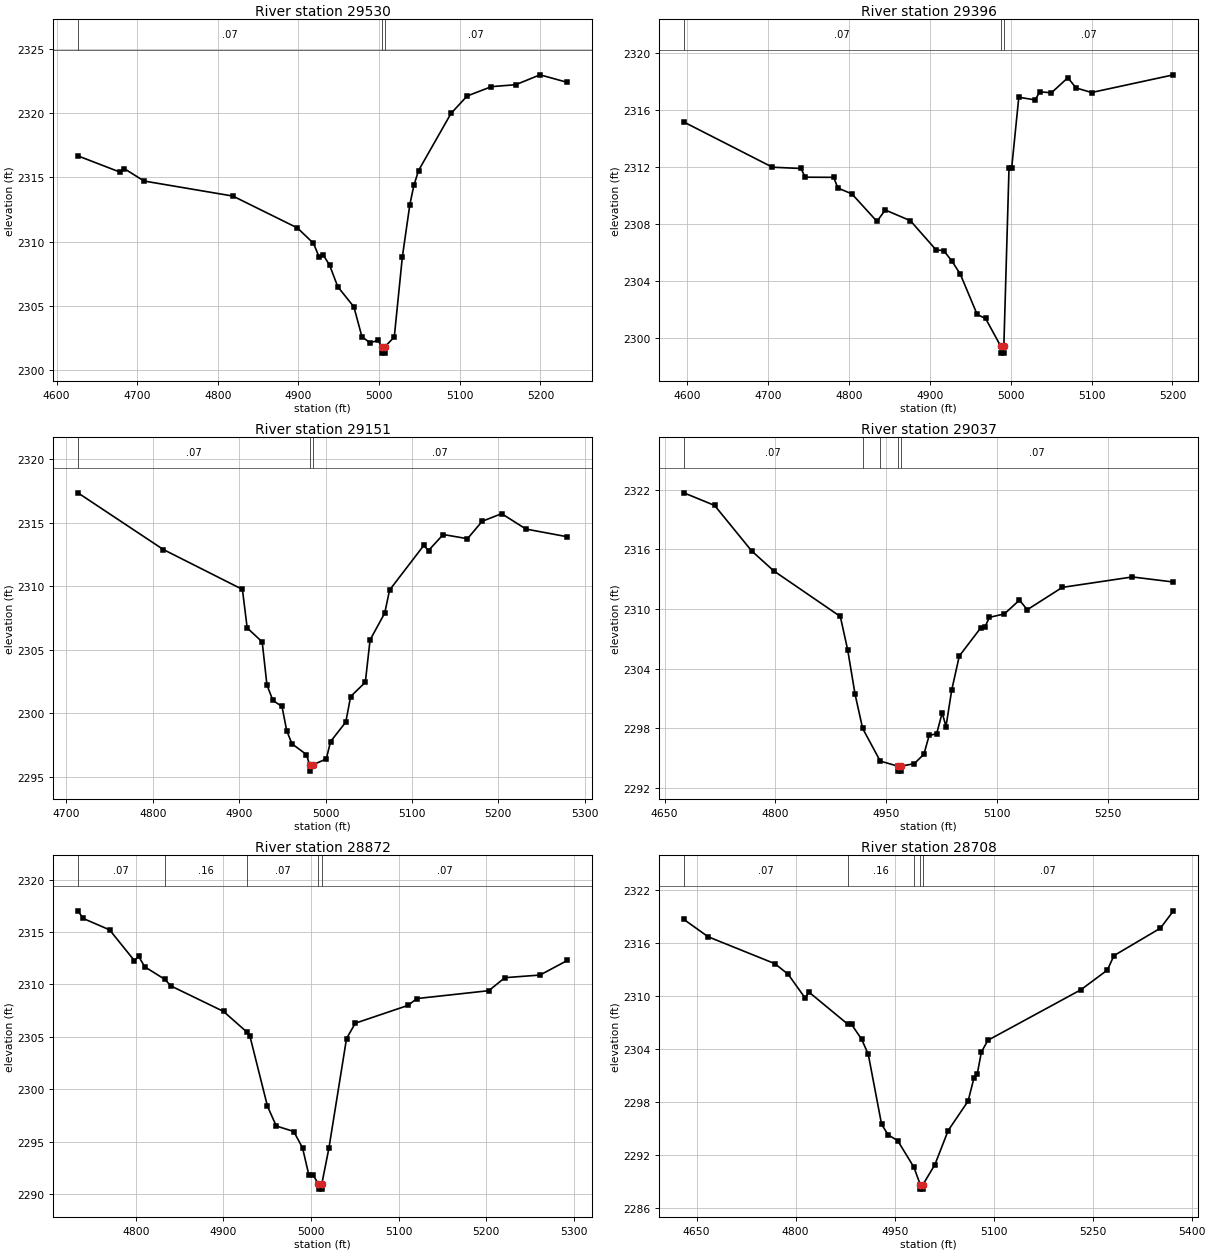
Type RM Length L Ch R = 1 ,29530   ,134,134,134
BEGIN DESCRIPTION:
590
END DESCRIPTION:
XS GIS Cut Line= 3
      1508316.99      6794645.38      1507936.74      6794629.75
      1507711.07      6794650.58
#Sta/Elev= 30
  4626.4 2316.68  4678.4 2315.42  4683.8 2315.69  4708.5 2314.72  4818.6 2313.55
  4898.6 2311.07  4918.6 2309.87  4925.7 2308.79  4930.7 2308.97  4938.7 2308.15
  4948.7 2306.49  4968.7 2304.92  4978.7 2302.59  4988.7 2302.13  4998.7 2302.31
  5003.3 2301.82  5003.6 2301.32  5007.1 2301.32  5007.3 2301.82  5018.8 2302.58
  5028.8 2308.81  5038.1 2312.89  5043.1 2314.38  5048.9 2315.54  5089.1 2319.98
  5109.1 2321.34  5139.3 2322.07  5169.4 2322.22  5199.5 2322.99  5233.6  2322.4
#Mann= 3 ,-1 , 0
  4626.4     .07       0  5003.3     .07       0  5007.3     .07       0
Bank Sta=5003.3,5007.3
XS Rating Curve= 0 ,0
Exp/Cntr=0.3,0.1

Type RM Length L Ch R = 1 ,29396   ,245,245,245
BEGIN DESCRIPTION:
589
END DESCRIPTION:
XS GIS Cut Line= 3
      1508296.15      6794610.66      1507903.76      6794508.22
      1507705.79       6794478.7
#Sta/Elev= 30
  4595.5 2315.13  4705.1 2311.96  4740.4 2311.87  4745.6 2311.26  4780.9 2311.25
    4786  2310.5  4803.4 2310.09  4834.4 2308.16  4844.7 2308.96  4875.7 2308.21
  4907.4 2306.17  4917.1  2306.1  4927.4 2305.36  4937.6 2304.45  4958.4 2301.63
  4968.8 2301.35  4987.4 2299.42  4987.7 2298.92  4991.2 2298.92  4991.4 2299.42
  4997.8 2311.92  5001.1 2311.92  5009.9 2316.87  5030.1 2316.68  5035.8 2317.25
  5050.3 2317.18  5070.6 2318.24  5080.7 2317.52    5100  2317.2  5201.2 2318.44
#Mann= 3 ,-1 , 0
  4595.5     .07       0  4987.4     .07       0  4991.4     .07       0
Bank Sta=4987.4,4991.4
XS Rating Curve= 0 ,0
Exp/Cntr=0.3,0.1

Type RM Length L Ch R = 1 ,29151   ,114,114,114
BEGIN DESCRIPTION:
588
END DESCRIPTION:
XS GIS Cut Line= 3
      1508389.82      6794584.59      1508120.77      6794459.61
      1507877.69      6794341.54
#Sta/Elev= 30
  4713.2 2317.35  4812.1 2312.89  4903.7 2309.75  4909.2 2306.72  4926.6 2305.62
  4932.1 2302.23    4939 2301.01  4949.5 2300.54    4955 2298.63  4961.1  2297.6
  4977.9 2296.75  4981.4 2295.95  4981.6 2295.45  4985.4 2295.95  5000.8 2296.41
  5005.8 2297.78  5023.4 2299.31    5029 2301.32    5046 2302.44  5051.5 2305.77
  5068.5 2307.89  5074.1  2309.7  5113.7 2313.21  5119.2 2312.81  5136.2 2314.07
  5164.3 2313.74  5181.3 2315.11  5203.9 2315.71    5232  2314.5  5280.1 2313.89
#Mann= 3 ,-1 , 0
  4713.2     .07       0  4981.4     .07       0  4985.4     .07       0
Bank Sta=4981.4,4985.4
XS Rating Curve= 0 ,0
Exp/Cntr=0.3,0.1

Type RM Length L Ch R = 1 ,29037   ,165,165,165
BEGIN DESCRIPTION:
587
END DESCRIPTION:
XS GIS Cut Line= 3
      1508516.62      6794376.28      1508191.95      6794378.01
      1507860.36      6794315.52
#Sta/Elev= 30
  4676.1  2321.7  4717.7 2320.43  4767.7 2315.86  4797.7 2313.84  4887.7 2309.25
  4897.7 2305.87  4907.7  2301.4  4917.9 2297.98  4941.7 2294.69  4965.7 2294.18
    4966 2293.68  4969.5 2293.68  4969.7 2294.18  4987.7 2294.43  5000.8 2295.39
  5007.8 2297.27    5018 2297.45  5025.5 2299.55  5030.6 2298.17  5038.4 2301.86
  5048.6 2305.27  5077.9 2308.13    5083 2308.15  5089.3 2309.16  5109.6 2309.51
    5130  2310.9  5140.5 2309.93  5187.9 2312.18  5282.6 2313.23  5338.2 2312.72
#Mann= 5 ,-1 , 0
  4676.1     .07       0  4917.9     .16       0  4941.7     .07       0
  4965.7     .07       0  4969.7     .07       0
Bank Sta=4965.7,4969.7
XS Rating Curve= 0 ,0
Exp/Cntr=0.3,0.1

Type RM Length L Ch R = 1 ,28872   ,164,164,164
BEGIN DESCRIPTION:
586
END DESCRIPTION:
XS GIS Cut Line= 3
       1508421.1      6794235.65      1508155.49      6794225.24
      1507863.87      6794251.27
#Sta/Elev= 30
    4734 2317.02  4740.1 2316.29  4770.1 2315.21  4798.4 2312.28  4803.4 2312.67
  4810.2 2311.69    4833  2310.5  4840.2 2309.86  4900.2 2307.43  4926.5 2305.49
  4930.3 2305.07  4950.3  2298.4  4960.3 2296.52  4980.3 2295.99  4990.3 2294.43
  4997.6 2291.82  5002.6 2291.82  5008.3    2291  5008.6  2290.5  5012.1  2290.5
  5012.3    2291  5020.4  2294.4  5040.5 2304.85  5050.5 2306.31  5110.7 2308.01
  5120.8 2308.66  5202.8 2309.41  5221.2 2310.65  5261.3  2310.9  5292.6  2312.3
#Mann= 5 ,-1 , 0
    4734     .07       0    4833     .16       0  4926.5     .07       0
  5008.3     .07       0  5012.3     .07       0
Bank Sta=5008.3,5012.3
XS Rating Curve= 0 ,0
Exp/Cntr=0.3,0.1

Type RM Length L Ch R = 1 ,28708   ,89,89,89
BEGIN DESCRIPTION:
585
END DESCRIPTION:
XS GIS Cut Line= 3
      1508471.46      6794129.75      1508103.41      6794075.93
      1507735.37      6794112.39
#Sta/Elev= 30
  4630.6 2318.63  4667.4 2316.67  4768.5 2313.63  4788.7 2312.43  4814.7 2309.71
  4819.8 2310.44  4879.5 2306.76  4884.7 2306.77  4899.9  2305.1    4910  2303.4
  4930.2 2295.48  4940.3 2294.28  4954.6 2293.64  4979.2 2290.63  4988.8 2288.66
  4989.1 2288.16  4992.6 2288.16  4992.8 2288.66    5011 2290.93  5031.1 2294.78
  5061.3 2298.11  5070.3 2300.76  5075.3 2301.22  5081.4 2303.65  5091.4 2304.98
  5232.1 2310.68  5272.2  2312.9  5282.3 2314.54  5352.7 2317.64  5372.4  2319.6
#Mann= 5 ,-1 , 0
  4630.6     .07       0  4879.5     .16       0  4979.2     .07       0
  4988.8     .07       0  4992.8     .07       0
Bank Sta=4988.8,4992.8
XS Rating Curve= 0 ,0
Exp/Cntr=0.3,0.1