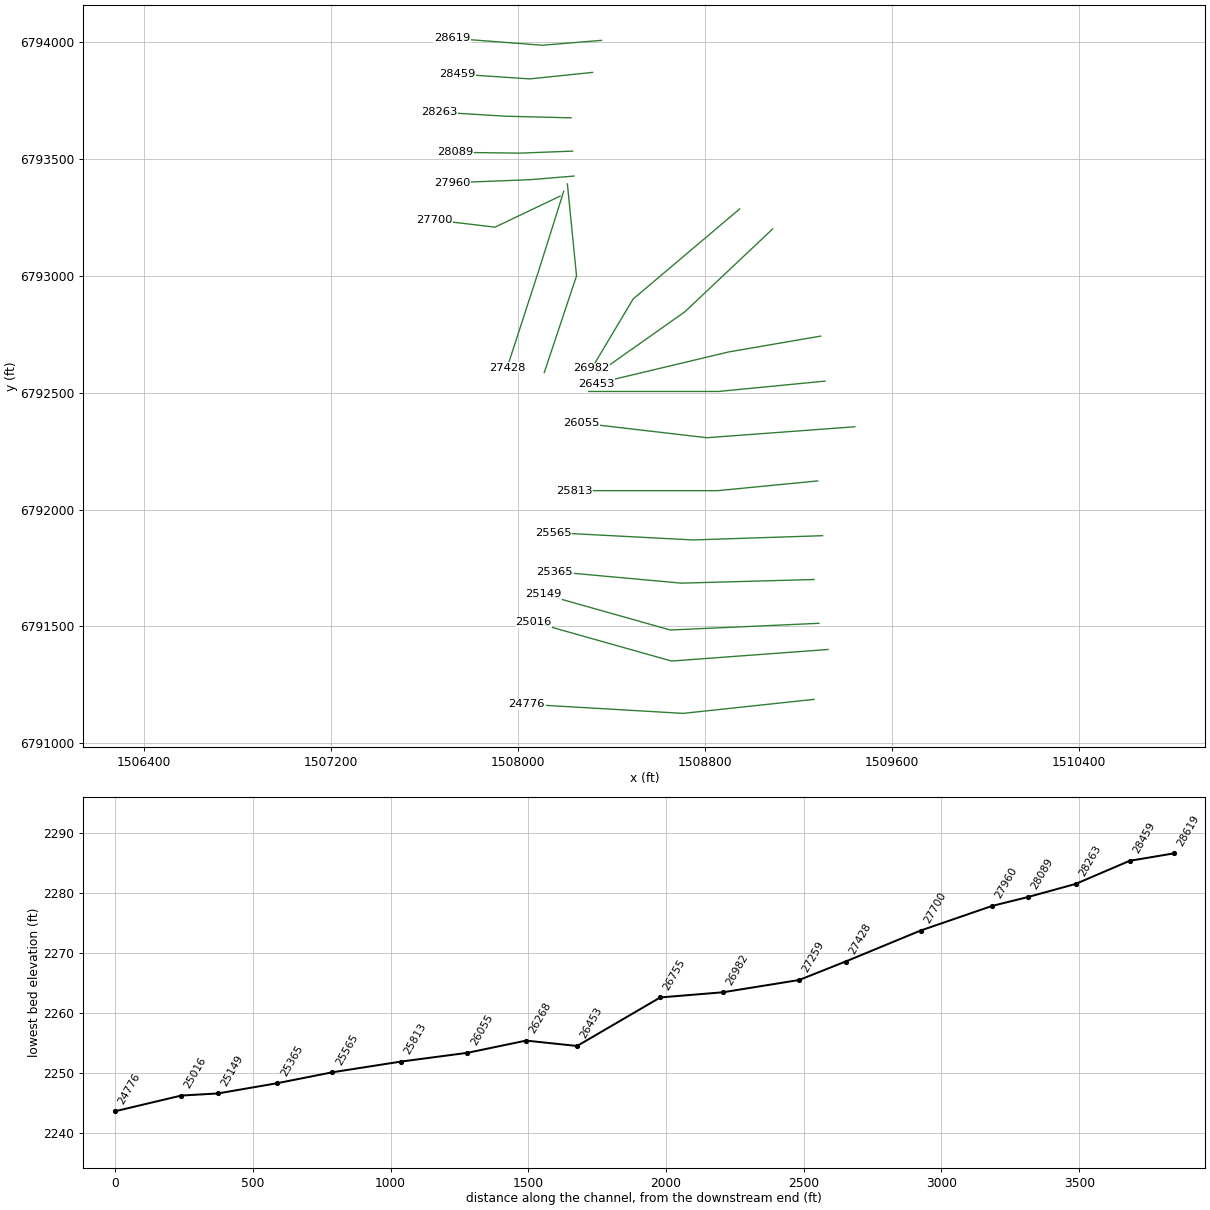
HEC-RAS study Cedar Creek 2.prj: Cedar Creek 2 Base Level Engineering

--- Cedar Creek 2.g01 (geometry) --- (continued)

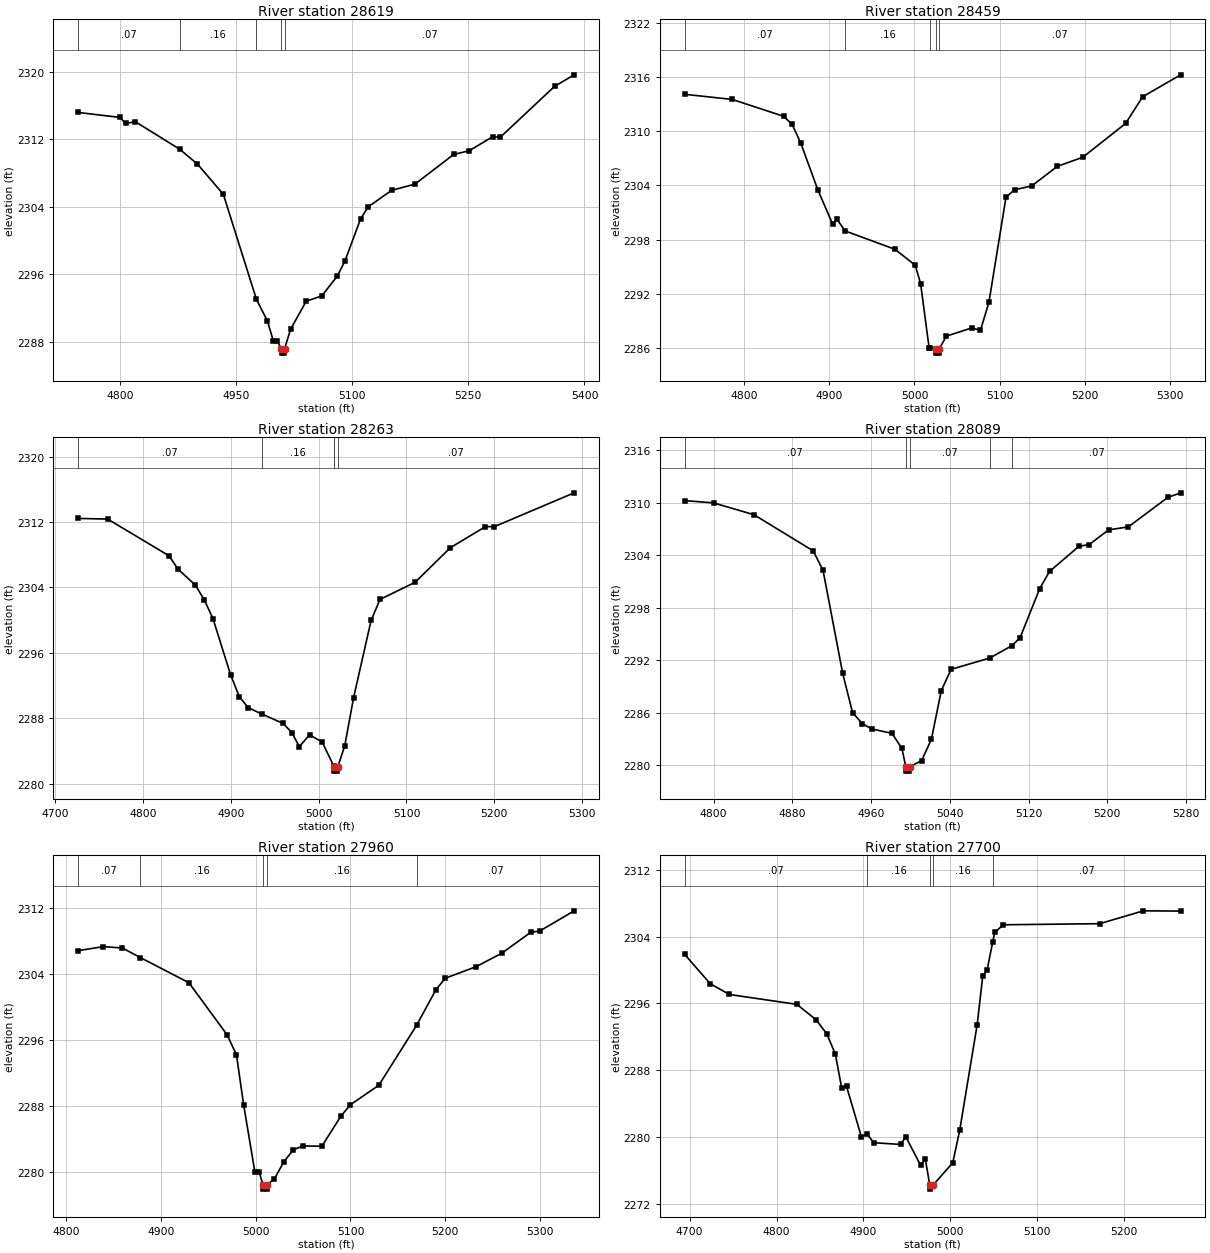
Type RM Length L Ch R = 1 ,28619   ,160,160,160
BEGIN DESCRIPTION:
584
END DESCRIPTION:
XS GIS Cut Line= 3
      1508358.61      6794008.22      1508105.14      6793987.39
       1507719.9      6794016.89
#Sta/Elev= 30
    4746 2315.18  4799.8 2314.59  4807.3 2313.87  4819.9 2314.08  4877.2 2310.81
  4900.1 2309.05  4933.5 2305.47  4976.3    2293  4990.4 2290.47  4997.9 2288.13
  5002.9 2288.13  5008.5 2287.14  5008.7 2286.64  5012.2 2286.64  5012.5 2287.14
  5020.5  2289.5  5040.6  2292.8  5060.6 2293.42  5080.7 2295.77  5090.7 2297.58
  5110.8 2302.57  5120.8    2304  5150.9 2305.94    5181 2306.68  5231.1  2310.2
  5251.2 2310.64  5281.3  2312.3  5291.3 2312.24  5361.5 2318.28  5386.7 2319.64
#Mann= 5 ,-1 , 0
    4746     .07       0  4877.2     .16       0  4976.3     .07       0
  5008.5     .07       0  5012.5     .07       0
Bank Sta=5008.5,5012.5
XS Rating Curve= 0 ,0
Exp/Cntr=0.3,0.1

Type RM Length L Ch R = 1 ,28459   ,196,196,196
BEGIN DESCRIPTION:
583
END DESCRIPTION:
XS GIS Cut Line= 3
      1508320.46      6793871.07      1508051.32      6793843.29
      1507740.59      6793864.12
#Sta/Elev= 30
  4730.3 2314.12  4786.1 2313.55  4846.4 2311.68  4856.4 2310.78  4866.5 2308.71
  4886.6 2303.51    4904 2299.69    4909 2300.24  4918.8 2298.95  4977.1 2296.92
  5000.9 2295.15  5007.2  2293.1  5017.2 2285.94    5018 2285.94  5025.3  2285.9
  5025.5  2285.4    5029  2285.4  5029.3  2285.9  5037.3 2287.28  5067.3  2288.2
  5077.4 2287.92  5087.4 2291.07  5107.4 2302.71  5117.5 2303.53  5137.5 2303.95
  5167.6 2306.12  5197.6 2307.14  5247.7 2310.88  5267.8 2313.85  5312.3 2316.28
#Mann= 5 ,-1 , 0
  4730.3     .07       0  4918.8     .16       0    5018     .07       0
  5025.3     .07       0  5029.3     .07       0
Bank Sta=5025.3,5029.3
XS Rating Curve= 0 ,0
Exp/Cntr=0.3,0.1

Type RM Length L Ch R = 1 ,28263   ,174,174,174
BEGIN DESCRIPTION:
582
END DESCRIPTION:
XS GIS Cut Line= 3
      1508228.45      6793676.62      1507950.63      6793683.57
      1507664.16      6793700.93
#Sta/Elev= 30
  4726.1 2312.44  4759.6 2312.36  4829.6 2307.87  4839.6 2306.26  4859.6 2304.27
  4869.6  2302.5  4879.6 2300.19  4899.6 2293.34  4909.6 2290.65  4919.6 2289.31
  4934.9 2288.54  4959.6 2287.37  4969.6 2286.23  4977.9 2284.54  4989.6 2285.97
    5004  2285.1  5017.2 2282.15  5017.7 2282.04  5017.9 2281.54  5021.4 2281.54
  5021.7 2282.04  5029.7 2284.64  5039.7 2290.49  5059.7 2299.96  5069.8 2302.53
  5109.8 2304.63  5149.9 2308.85    5190 2311.44    5200 2311.43    5291 2315.57
#Mann= 5 ,-1 , 0
  4726.1     .07       0  4934.9     .16       0  5017.2     .07       0
  5017.7     .07       0  5021.7     .07       0
Bank Sta=5017.7,5021.7
XS Rating Curve= 0 ,0
Exp/Cntr=0.3,0.1

Type RM Length L Ch R = 1 ,28089   ,129,129,129
BEGIN DESCRIPTION:
581
END DESCRIPTION:
XS GIS Cut Line= 3
      1508235.39      6793534.26      1508007.92      6793525.58
      1507731.88      6793529.06
#Sta/Elev= 30
  4770.7 2310.24    4800 2309.98  4841.1 2308.63  4901.2  2304.5  4911.2 2302.29
  4931.2  2290.5  4941.2 2286.03  4951.2 2284.75  4961.2 2284.14  4981.2 2283.66
  4991.3 2281.94  4995.3 2279.84  4995.5 2279.34    4999 2279.34  4999.3 2279.84
  5011.3 2280.54  5021.3 2282.98  5031.3 2288.53  5041.3 2290.97  5080.6 2292.26
  5103.2 2293.68  5111.3 2294.57  5131.3 2300.19  5141.3 2302.15  5171.3 2305.04
  5181.3  2305.2  5201.3  2306.9  5221.3 2307.24  5261.3  2310.6  5274.4 2311.13
#Mann= 5 ,-1 , 0
  4770.7     .07       0  4995.3     .07       0  4999.3     .07       0
  5080.6     .16       0  5103.2     .07       0
Bank Sta=4995.3,4999.3
XS Rating Curve= 0 ,0
Exp/Cntr=0.3,0.1

Type RM Length L Ch R = 1 ,27960   ,260,260,260
BEGIN DESCRIPTION:
580
END DESCRIPTION:
XS GIS Cut Line= 3
      1508241.44      6793427.49      1508051.32      6793411.87
      1507719.03      6793398.89
#Sta/Elev= 30
  4812.7 2306.79  4839.2 2307.28  4859.3 2307.11  4878.3 2305.95  4929.5  2302.9
  4969.7  2296.6  4979.7 2294.15  4987.2 2288.13  4999.1 2279.96  5003.5 2279.96
  5007.8 2278.37    5008 2277.87  5011.5 2277.87  5011.8 2278.37  5019.8 2279.13
  5029.8 2281.21  5039.8 2282.65  5049.8 2283.11  5069.8 2283.07  5089.8 2286.71
  5099.9  2288.1  5129.9 2290.47  5169.7 2297.73  5189.9    2302  5199.9 2303.44
  5232.8 2304.86    5260 2306.51    5290    2309    5300 2309.19    5336 2311.62
#Mann= 5 ,-1 , 0
  4812.7     .07       0  4878.3     .16       0  5007.8     .07       0
  5011.8     .16       0  5169.7     .07       0
Bank Sta=5007.8,5011.8
XS Rating Curve= 0 ,0
Exp/Cntr=0.3,0.1

Type RM Length L Ch R = 1 ,27700   ,272,272,272
BEGIN DESCRIPTION:
579
END DESCRIPTION:
XS GIS Cut Line= 3
       1508181.5      6793341.54      1507902.89      6793208.74
       1507642.5      6793239.99
#Sta/Elev= 30
  4694.3 2301.86  4723.7 2298.35  4745.8 2297.06  4823.4 2295.88  4845.5 2294.04
  4857.9 2292.35  4867.7 2289.93    4875 2285.89  4880.6 2286.07  4897.7 2280.02
  4904.4 2280.32    4912 2279.31  4943.1  2279.1  4948.7 2280.05  4965.8 2276.62
  4971.4 2277.32  4976.4 2274.25  4976.7 2273.75  4980.4 2274.25  5002.9 2276.91
  5010.9 2280.79    5031 2293.44  5037.4 2299.26  5042.4 2300.01    5049 2303.39
  5051.2 2304.51  5061.2 2305.41    5172 2305.54  5222.4 2307.08  5265.2 2307.05
#Mann= 5 ,-1 , 0
  4694.3     .07       0  4904.4     .16       0  4976.4     .07       0
  4980.4     .16       0    5049     .07       0
Bank Sta=4976.4,4980.4
XS Rating Curve= 0 ,0
Exp/Cntr=0.3,0.1

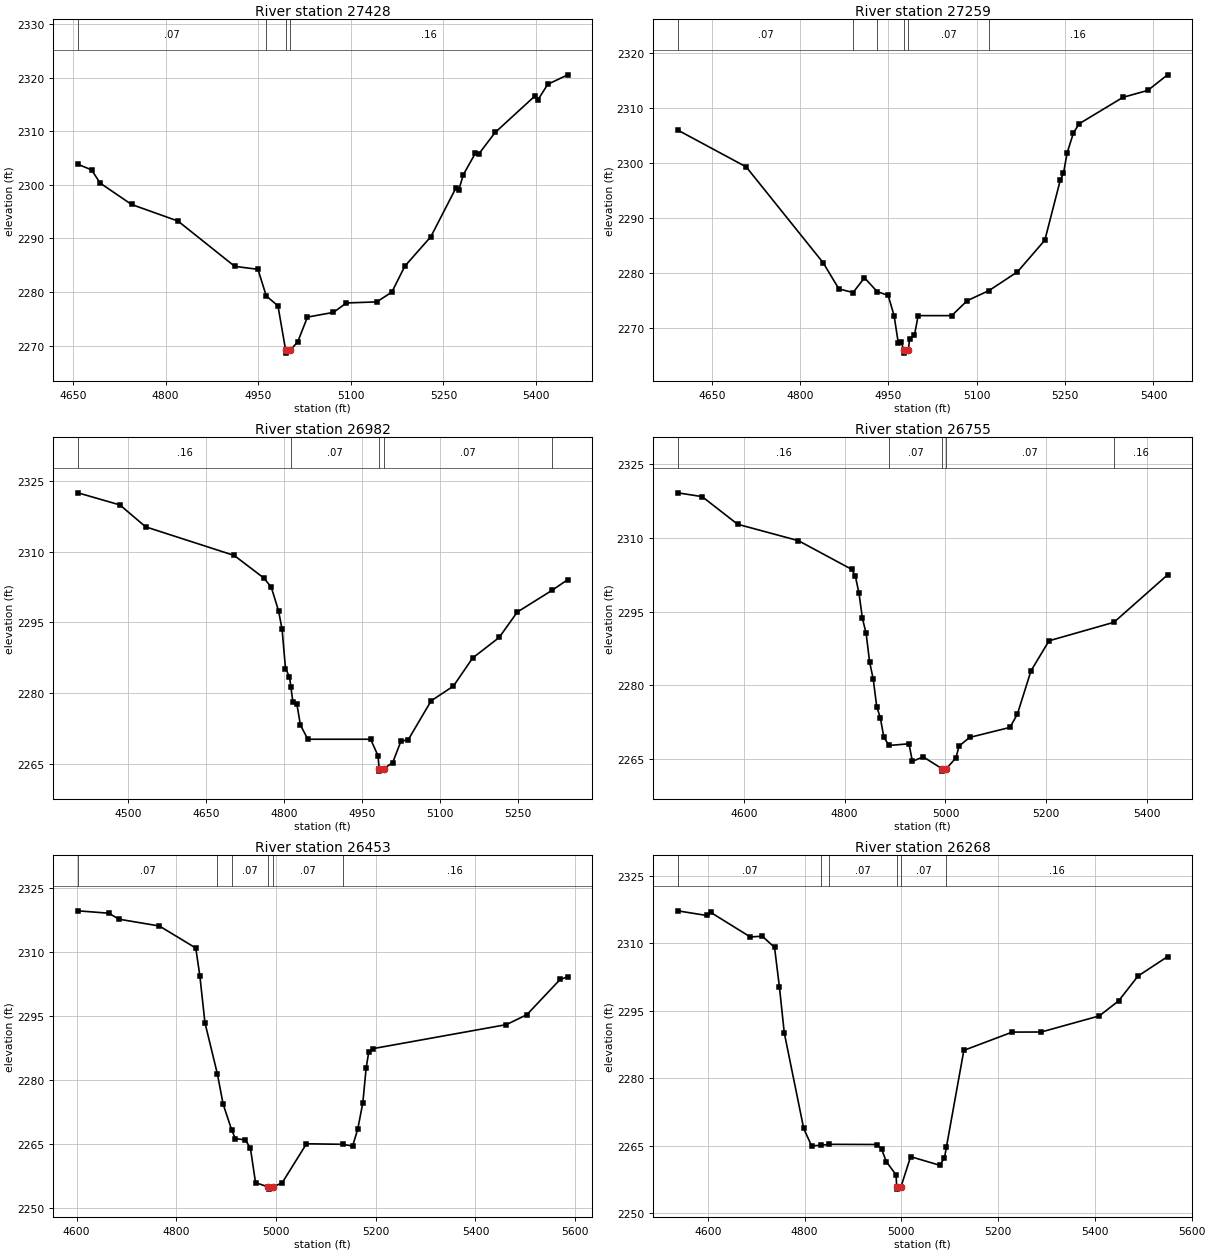
Type RM Length L Ch R = 1 ,27428   ,169,169,169
BEGIN DESCRIPTION:
578
END DESCRIPTION:
XS GIS Cut Line= 3
      1508197.15      6793362.37      1508092.99      6793031.66
      1507954.97      6792607.16
#Sta/Elev= 30
  4658.1 2303.85  4680.2 2302.81  4694.1 2300.34  4744.9 2296.35  4820.1 2293.25
    4912 2284.79  4949.6 2284.23  4963.1 2279.25    4982 2277.41  4994.5 2269.08
    4995 2268.58  5001.8 2269.08  5014.2 2270.74  5029.7 2275.31  5071.8 2276.19
  5092.8 2277.95    5142 2278.15  5166.4 2279.98  5187.4 2284.82  5229.5 2290.32
  5269.8 2299.35    5275 2299.14  5282.1  2301.9  5301.7 2305.93    5307 2305.75
  5333.6 2309.79  5397.5 2316.55  5402.8 2315.87  5418.8 2318.79  5451.2 2320.56
#Mann= 4 ,-1 , 0
  4658.1     .07       0  4963.1     .16       0  4994.5     .07       0
  5001.8     .16       0
Bank Sta=4994.5,5001.8
XS Rating Curve= 0 ,0
Exp/Cntr=0.3,0.1

Type RM Length L Ch R = 1 ,27259   ,277,277,277
BEGIN DESCRIPTION:
577
END DESCRIPTION:
XS GIS Cut Line= 3
      1508212.78      6793393.69      1508251.85      6793000.41
      1508113.82      6792586.32
#Sta/Elev= 30
  4592.2 2306.06  4708.5 2299.36  4839.1 2281.94  4865.9 2277.17    4890 2276.51
  4909.4 2279.19  4930.8 2276.69  4949.6 2275.98  4959.7 2272.28  4966.7 2267.38
  4971.8 2267.54  4976.1 2265.99  4976.6 2265.49  4983.5 2265.99  4986.1 2268.05
  4994.2 2268.75  5000.5 2272.31  5057.5 2272.31  5083.8 2275.03  5120.9 2276.87
  5169.1 2280.27  5215.6 2286.03  5241.9 2296.99  5247.2 2298.17  5253.5 2301.93
    5264 2305.48  5273.6 2307.18  5348.3 2312.01  5390.5 2313.27  5423.9  2316.1
#Mann= 6 ,-1 , 0
  4592.2     .07       0    4890     .16       0  4930.8     .07       0
  4976.1     .07       0  4983.5     .07       0  5120.9     .16       0
Bank Sta=4976.1,4983.5
XS Rating Curve= 0 ,0
Exp/Cntr=0.3,0.1

Type RM Length L Ch R = 1 ,26982   ,227,227,227
BEGIN DESCRIPTION:
576
END DESCRIPTION:
XS GIS Cut Line= 3
      1508949.76      6793286.86      1508494.03      6792901.45
      1508316.96       6792604.6
#Sta/Elev= 30
    4403 2322.52  4483.8 2319.95  4533.3  2315.3  4703.6 2309.23  4760.7 2304.44
    4775  2302.5    4789 2297.49  4795.9 2293.52  4802.4 2285.21  4810.1 2283.47
  4812.7 2281.35  4816.7 2278.08  4824.4 2277.63    4831 2273.27  4845.3 2270.21
  4966.2 2270.21  4980.4 2266.72  4982.6 2263.94  4983.1 2263.44  4991.4 2263.94
  5008.7 2265.26  5024.3 2269.74  5038.8 2270.15  5082.7 2278.37  5125.5 2281.49
  5162.5 2287.46  5213.5 2291.81  5248.4 2297.21  5315.5 2301.84  5345.5 2304.09
#Mann= 5 ,-1 , 0
    4403     .16       0  4812.7     .07       0  4982.6     .07       0
  4991.4     .07       0  5315.5     .16       0
Bank Sta=4982.6,4991.4
XS Rating Curve= 0 ,0
Exp/Cntr=0.3,0.1

Type RM Length L Ch R = 1 ,26755   ,302,302,302
BEGIN DESCRIPTION:
575
END DESCRIPTION:
XS GIS Cut Line= 3
       1509090.4      6793200.94      1508715.39      6792846.76
      1508343.03      6792583.77
#Sta/Elev= 30
  4468.8 2319.18  4517.3 2318.41  4587.7 2312.79  4708.3 2309.45  4814.3  2303.6
  4821.2 2302.24  4828.4 2298.81  4835.3 2293.63  4842.6 2290.63  4849.5  2284.8
  4856.8 2281.26  4863.6 2275.72  4870.9 2273.39  4877.8 2269.43  4888.4  2267.8
  4927.6 2268.14  4934.4 2264.57  4955.9 2265.48  4992.9 2263.08  4993.4 2262.58
  5001.7 2263.08  5020.8 2265.28  5026.9 2267.67  5047.8 2269.43  5127.9 2271.47
  5142.6 2274.16  5169.7 2282.99  5205.5 2289.09  5334.2 2292.85  5440.5 2302.49
#Mann= 5 ,-1 , 0
  4468.8     .16       0  4888.4     .07       0  4992.9     .07       0
  5001.7     .07       0  5334.2     .16       0
Bank Sta=4992.9,5001.7
XS Rating Curve= 0 ,0
Exp/Cntr=0.3,0.1

Type RM Length L Ch R = 1 ,26453   ,185,185,185
BEGIN DESCRIPTION:
574
END DESCRIPTION:
XS GIS Cut Line= 3
      1509296.09      6792742.59      1508902.89      6792674.89
       1508335.2      6792539.48
#Sta/Elev= 30
  4602.5 2319.69  4664.5 2319.13  4684.8 2317.73    4766 2316.13  4838.9 2310.97
  4847.1 2304.47  4857.3 2293.48  4882.1 2281.56  4893.8 2274.39  4910.7 2268.43
  4918.2 2266.32  4938.5    2266  4948.6 2264.02  4958.8 2255.98  4984.8 2254.97
  4985.3 2254.47  4993.6 2254.97  5012.2 2255.95    5061  2265.1  5133.7 2264.97
  5153.5 2264.56  5163.8 2268.51  5174.1 2274.76  5180.6 2282.79  5185.8 2286.53
  5194.6  2287.4  5461.9 2293.02  5503.1 2295.35  5569.9 2303.62  5585.1 2304.21
#Mann= 6 ,-1 , 0
  4602.5     .07       0  4882.1     .16       0  4910.7     .07       0
  4984.8     .07       0  4993.6     .07       0  5133.7     .16       0
Bank Sta=4984.8,4993.6
XS Rating Curve= 0 ,0
Exp/Cntr=0.3,0.1

Type RM Length L Ch R = 1 ,26268   ,213,213,213
BEGIN DESCRIPTION:
573
END DESCRIPTION:
XS GIS Cut Line= 3
      1509314.31      6792549.88      1508858.62      6792505.62
      1508303.96      6792505.62
#Sta/Elev= 30
  4537.6 2317.24  4597.2 2316.21  4605.5 2316.92  4687.6 2311.44  4712.5 2311.59
  4737.8 2309.12  4747.9 2300.32  4757.9 2290.13  4798.1 2268.85  4814.4 2264.98
  4833.8 2265.12    4851 2265.33  4948.8 2265.29  4958.9 2264.33  4968.9 2261.47
    4989 2258.54  4990.3 2255.87  4990.8 2255.37  4999.1 2255.87  5019.1 2262.59
  5079.1 2260.68  5089.1 2262.33  5093.2 2264.79  5129.1 2286.22  5229.1 2290.28
  5289.1  2290.3  5409.1 2293.88  5449.1 2297.23  5489.1 2302.74  5550.1 2307.05
#Mann= 6 ,-1 , 0
  4537.6     .07       0  4833.8     .16       0    4851     .07       0
  4990.3     .07       0  4999.1     .07       0  5093.2     .16       0
Bank Sta=4990.3,4999.1
XS Rating Curve= 0 ,0
Exp/Cntr=0.3,0.1

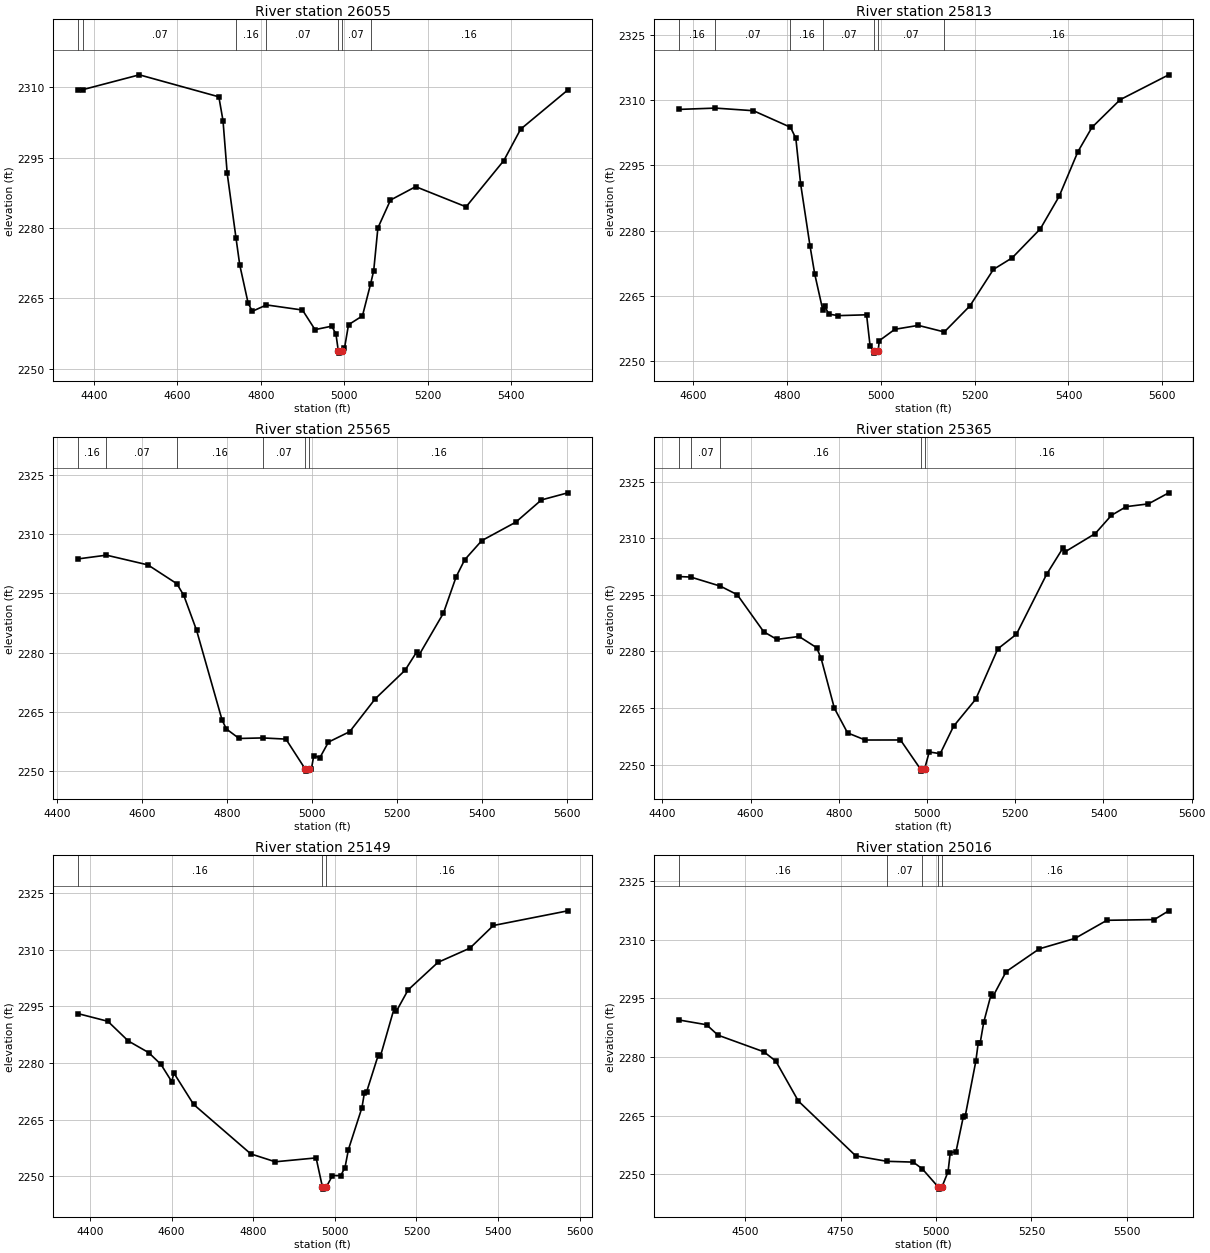
Type RM Length L Ch R = 1 ,26055   ,242,242,242
BEGIN DESCRIPTION:
572
END DESCRIPTION:
XS GIS Cut Line= 3
      1509441.94      6792354.57      1508809.14       6792307.7
       1508272.7       6792370.2
#Sta/Elev= 30
  4361.6  2309.5  4372.9 2309.51  4508.9 2312.68  4699.5 2307.99  4709.5  2302.9
  4719.5 2291.69  4740.7 2277.84  4749.6 2272.14  4769.7    2264  4779.7 2262.25
  4813.7 2263.61    4900 2262.52  4930.1 2258.34  4970.2 2259.08  4980.2 2257.43
  4985.9 2253.83  4986.4 2253.33  4994.7 2253.83  5000.7 2254.35  5010.4 2259.39
  5043.8 2261.27  5063.4 2268.11  5070.8 2270.91  5080.8 2280.02    5111 2285.97
  5171.4 2288.83  5292.3 2284.53  5382.7 2294.39  5423.1 2301.09  5536.2 2309.45
#Mann= 7 ,-1 , 0
  4361.6     .16       0  4372.9     .07       0  4740.7     .16       0
  4813.7     .07       0  4985.9     .07       0  4994.7     .07       0
  5063.4     .16       0
Bank Sta=4985.9,4994.7
XS Rating Curve= 0 ,0
Exp/Cntr=0.3,0.1

Type RM Length L Ch R = 1 ,25813   ,248,248,248
BEGIN DESCRIPTION:
571
END DESCRIPTION:
XS GIS Cut Line= 3
      1509283.13      6792122.81      1508856.01      6792081.14
      1508241.46      6792081.14
#Sta/Elev= 30
  4569.9 2307.82  4647.8 2308.12  4728.8 2307.52  4807.8 2303.72  4819.2 2301.18
  4829.3 2290.79  4849.3 2276.54  4859.4 2270.04  4876.5  2261.8  4880.7 2262.65
  4889.5 2260.81  4909.6 2260.47  4969.9 2260.66  4977.4 2253.48  4985.6 2252.36
  4986.1 2251.86  4994.5 2252.36    4997 2254.72  5030.1 2257.33  5080.1 2258.23
  5135.5 2256.72  5190.1 2262.71  5240.1 2271.08  5280.1 2273.74  5340.1  2280.4
  5380.1 2287.85  5420.1 2298.11  5450.1  2303.7  5510.1 2310.05  5613.6 2315.76
#Mann= 7 ,-1 , 0
  4569.9     .16       0  4647.8     .07       0  4807.8     .16       0
  4876.5     .07       0  4985.6     .07       0  4994.5     .07       0
  5135.5     .16       0
Bank Sta=4985.6,4994.5
XS Rating Curve= 0 ,0
Exp/Cntr=0.3,0.1

Type RM Length L Ch R = 1 ,25565   ,200,200,200
BEGIN DESCRIPTION:
570
END DESCRIPTION:
XS GIS Cut Line= 3
      1509303.93      6791888.43      1508749.24       6791870.2
      1508152.85      6791901.45
#Sta/Elev= 30
  4449.3  2303.7  4516.5 2304.65    4614 2302.19    4682 2297.43  4698.4 2294.46
  4728.4 2285.66  4788.4 2262.98  4798.4 2260.74  4828.4 2258.33  4883.8 2258.47
  4938.5 2258.17  4984.1 2250.58  4984.6 2250.08    4993 2250.58  4998.5 2250.66
  5003.9 2253.95  5018.5  2253.5  5038.6 2257.42  5088.6 2260.06  5148.7 2268.37
  5218.8 2275.58  5246.4 2280.25  5251.4 2279.38  5308.9 2289.99    5339 2299.22
    5359 2303.49  5399.1 2308.32  5479.2 2312.99  5539.3  2318.6  5601.5  2320.4
#Mann= 6 ,-1 , 0
  4449.3     .16       0  4516.5     .07       0    4682     .16       0
  4883.8     .07       0  4984.1     .07       0    4993     .16       0
Bank Sta=4984.1,4993
XS Rating Curve= 0 ,0
Exp/Cntr=0.3,0.1

Type RM Length L Ch R = 1 ,25365   ,216,216,216
BEGIN DESCRIPTION:
568
END DESCRIPTION:
XS GIS Cut Line= 3
      1509267.43      6791700.93      1508699.76      6791685.31
       1508159.1      6791734.69
#Sta/Elev= 30
  4437.2 2299.85  4464.1 2299.72  4531.4 2297.31  4569.7 2295.04  4629.7 2285.21
  4659.7 2283.18  4709.7 2283.97  4749.7 2280.99  4759.8 2278.18  4789.8 2264.97
  4819.8  2258.4  4859.8 2256.51  4939.8 2256.52  4985.4 2248.76  4985.9 2248.26
  4994.3 2248.76    5005 2253.34  5029.9 2252.89  5060.1 2260.15  5110.3 2267.31
  5160.5 2280.69  5202.6 2284.54  5270.9  2300.4  5307.8 2307.35  5312.8  2306.4
  5381.4 2311.25    5418 2316.08  5451.7 2318.39  5501.9 2319.12    5548 2322.05
#Mann= 5 ,-1 , 0
  4437.2     .16       0  4464.1     .07       0  4531.4     .16       0
  4985.4     .07       0  4994.3     .16       0
Bank Sta=4985.4,4994.3
XS Rating Curve= 0 ,0
Exp/Cntr=0.3,0.1

Type RM Length L Ch R = 1 ,25149   ,133,133,133
BEGIN DESCRIPTION:
569
END DESCRIPTION:
XS GIS Cut Line= 3
      1509288.34      6791513.43      1508652.89      6791484.78
      1508109.33      6791638.23
#Sta/Elev= 30
  4370.2 2293.08  4443.6 2291.04  4493.7 2285.82  4543.7 2282.73  4573.7 2279.62
  4600.3 2275.02  4605.3 2277.35  4653.8    2269    4794 2255.88    4854 2253.79
  4954.1 2254.82  4969.7 2247.04  4970.2 2246.54  4978.7 2247.04  4994.2 2250.13
  5014.5 2250.14  5024.9 2252.26  5033.3 2257.04  5066.4 2268.13  5072.5 2272.08
  5077.7 2272.26  5106.5  2282.1  5111.7 2281.76  5145.7 2294.59  5150.9 2293.73
  5179.7 2299.37  5252.8 2306.67  5331.2 2310.44  5388.6 2316.44  5571.1 2320.33
#Mann= 3 ,-1 , 0
  4370.2     .16       0  4969.7     .07       0  4978.7     .16       0
Bank Sta=4969.7,4978.7
XS Rating Curve= 0 ,0
Exp/Cntr=0.3,0.1

Type RM Length L Ch R = 1 ,25016   ,240,240,240
BEGIN DESCRIPTION:
567
END DESCRIPTION:
XS GIS Cut Line= 3
       1509327.4      6791401.45       1508658.1      6791351.97
      1508068.51       6791518.2
#Sta/Elev= 30
  4326.2 2289.44  4398.8 2288.22  4428.9 2285.55  4549.2 2281.29  4580.4 2278.91
  4639.4 2268.71  4789.9 2254.69  4871.5  2253.3  4940.3  2253.1  4963.9  2251.4
  5006.4 2246.69  5006.9 2246.19  5015.4 2246.69  5031.7 2250.63  5037.4  2255.5
  5052.5 2255.78  5071.4 2264.58  5076.6 2264.84  5104.4 2278.87  5110.7 2283.55
  5115.8 2283.55  5125.2 2288.88  5144.7 2296.05  5149.9 2295.56  5183.9  2301.8
  5270.7 2307.62  5364.2 2310.29  5447.9 2314.92    5572  2315.1  5609.9 2317.34
#Mann= 5 ,-1 , 0
  4326.2     .16       0  4871.5     .07       0  4963.9     .16       0
  5006.4     .07       0  5015.4     .16       0
Bank Sta=5006.4,5015.4
XS Rating Curve= 0 ,0
Exp/Cntr=0.3,0.1

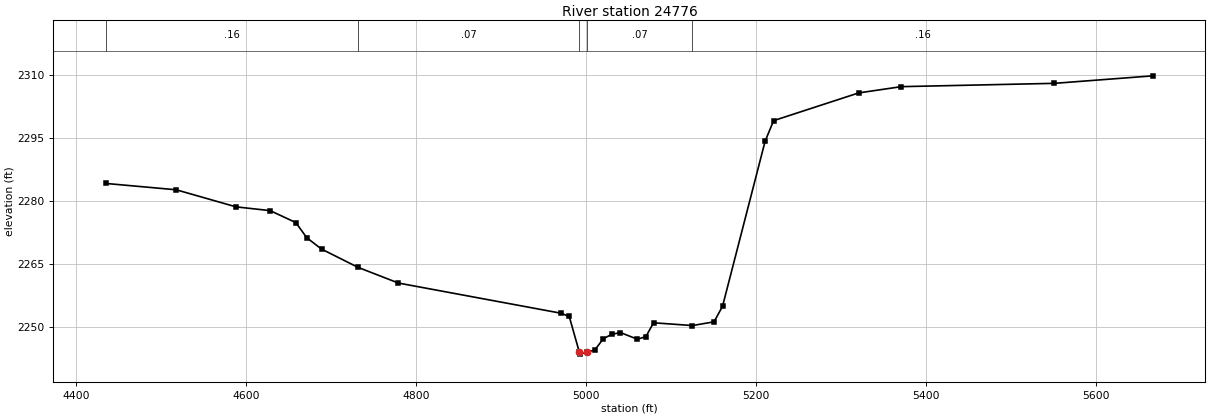
Type RM Length L Ch R = 1 ,24776   ,187,187,187
BEGIN DESCRIPTION:
566
END DESCRIPTION:
XS GIS Cut Line= 3
      1509267.43      6791187.91      1508707.57      6791128.01
      1508039.16      6791167.03
#Sta/Elev= 30
  4434.8 2284.25  4517.7 2282.74  4588.1 2278.67  4628.3 2277.77  4658.5 2274.92
  4671.3 2271.32  4688.7 2268.61  4731.6 2264.26  4779.2 2260.51  4970.3 2253.33
  4980.3 2252.54  4992.1 2244.07  4992.6 2243.57  5001.1 2244.07  5010.4 2244.56
  5020.5 2247.27  5030.5  2248.3  5040.5 2248.71  5060.5 2247.12  5070.5 2247.75
  5079.5 2251.04  5125.3 2250.38  5150.7 2251.27  5160.7 2254.97  5210.8  2294.3
  5220.8 2299.22    5321 2305.83  5371.1 2307.32  5551.4 2308.11  5667.4  2309.9
#Mann= 5 ,-1 , 0
  4434.8     .16       0  4731.6     .07       0  4992.1     .07       0
  5001.1     .07       0  5125.3     .16       0
Bank Sta=4992.1,5001.1
XS Rating Curve= 0 ,0
Exp/Cntr=0.3,0.1