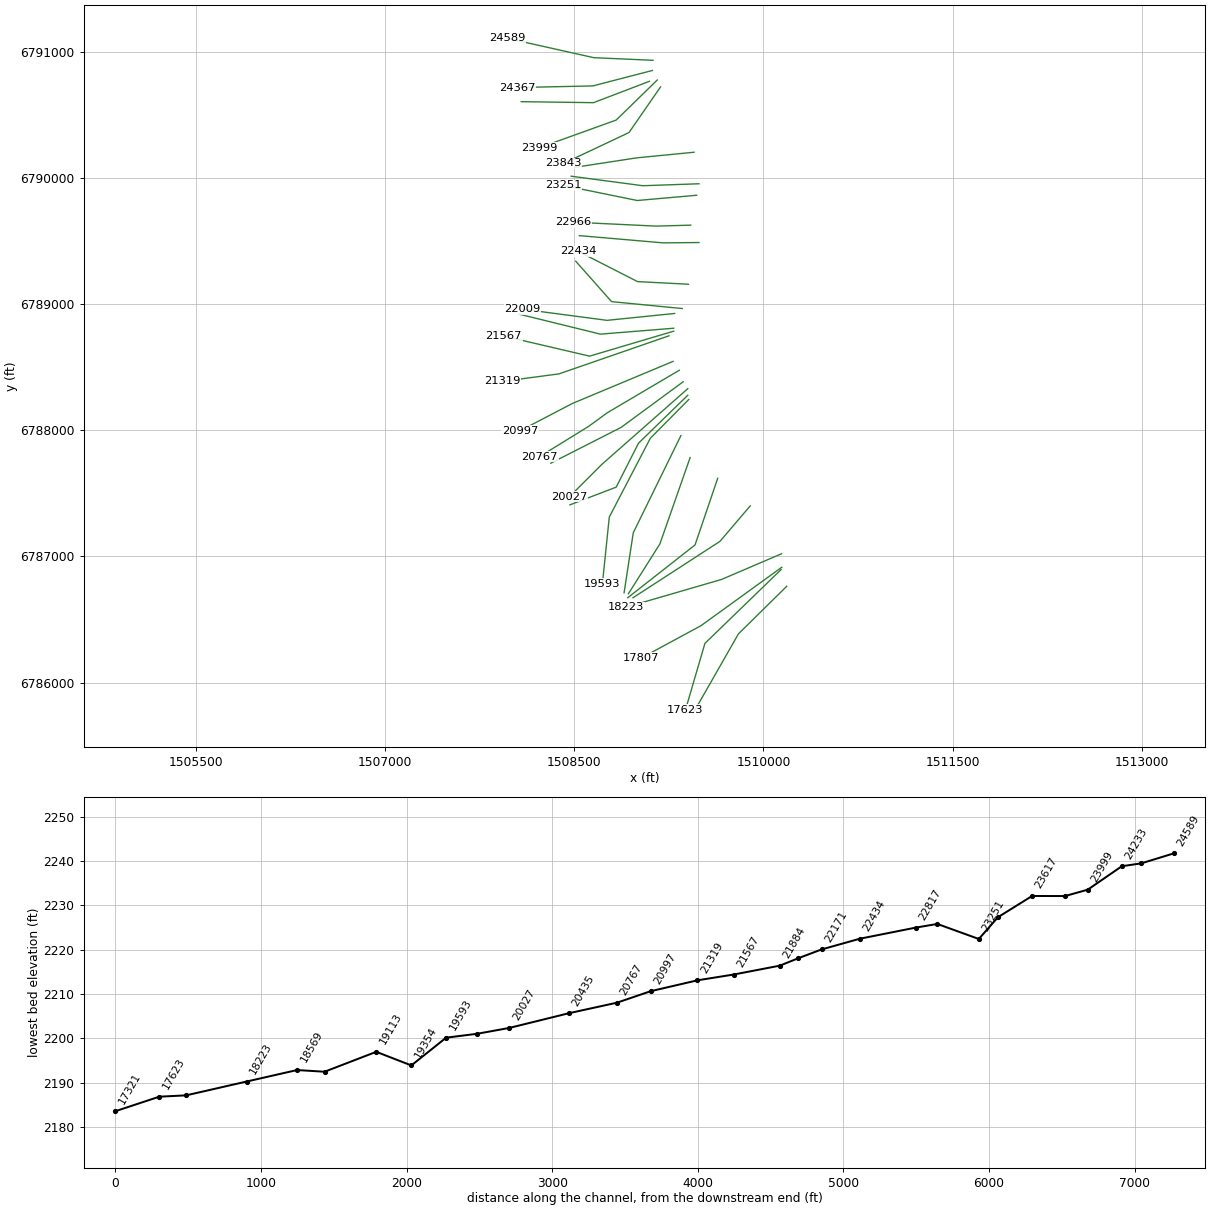
HEC-RAS study Cedar Creek 2.prj: Cedar Creek 2 Base Level Engineering

--- Cedar Creek 2.g01 (geometry) --- (continued)

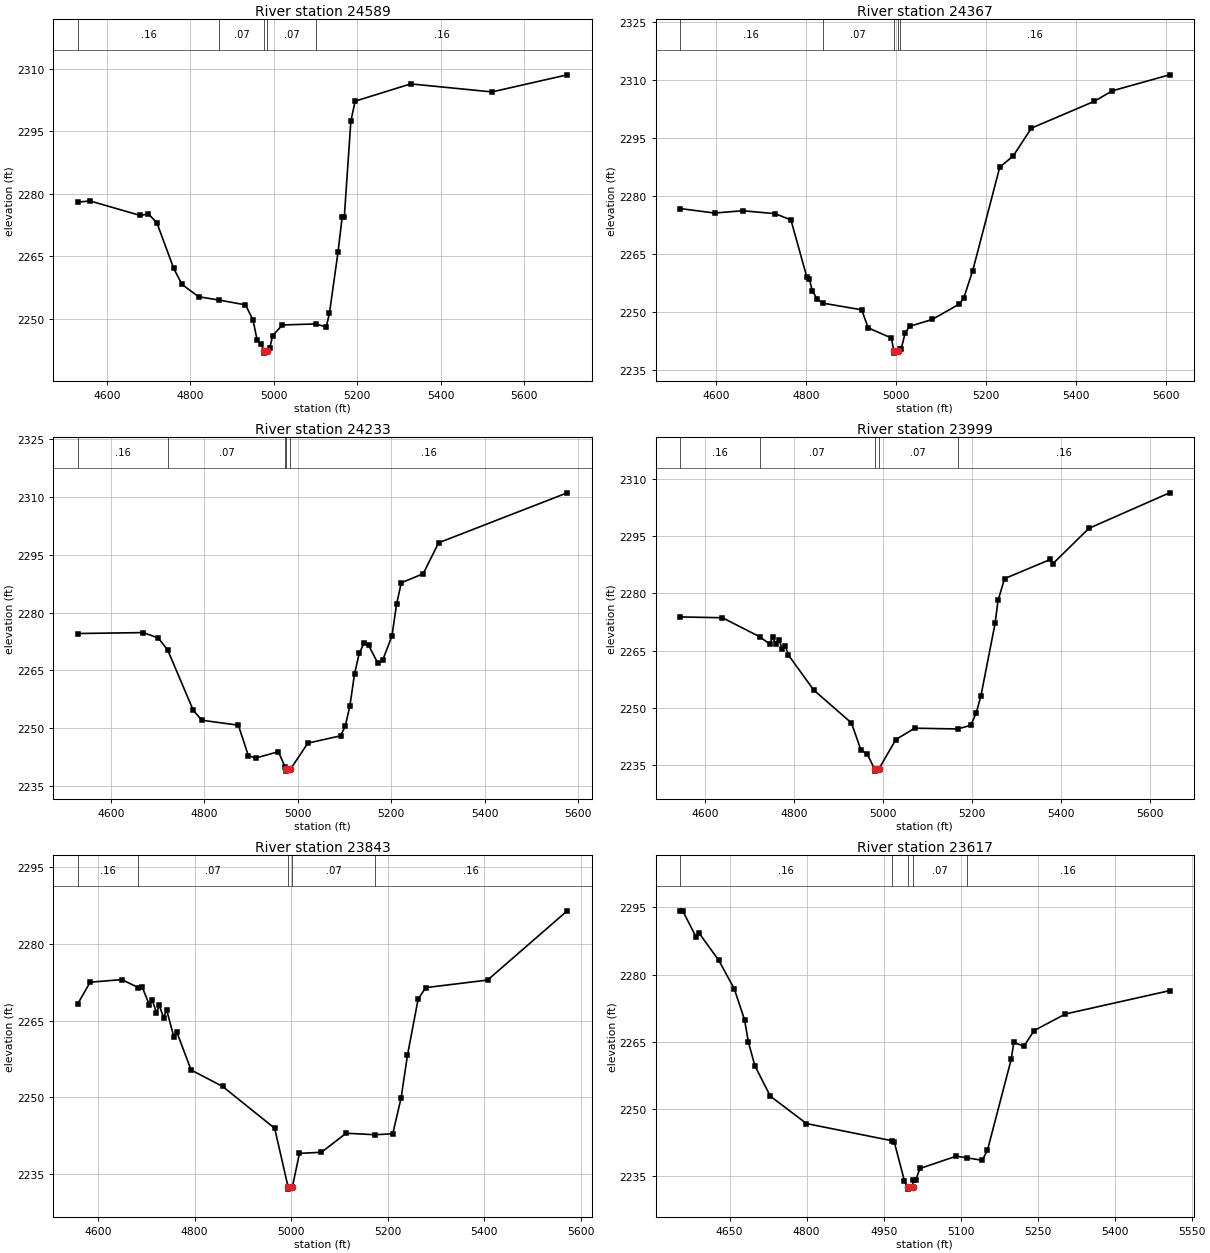
Type RM Length L Ch R = 1 ,24589   ,222,222,222
BEGIN DESCRIPTION:
564
END DESCRIPTION:
XS GIS Cut Line= 3
      1509124.25       6790935.3      1508655.49      6790956.14
      1507968.95      6791109.57
#Sta/Elev= 30
  4530.8 2277.99  4560.1 2278.26  4680.2 2274.78  4699.7 2275.15  4720.2    2273
  4760.3 2262.09  4780.3 2258.19  4820.3 2255.24  4869.9 2254.43  4932.4 2253.29
  4950.5 2249.67  4960.5 2244.73  4970.5 2243.94    4976 2242.19  4976.5 2241.69
    4985 2242.19  4990.5 2242.93  4997.8 2245.92    5021 2248.46  5101.7 2248.71
  5125.9 2247.93  5133.7 2251.31  5154.2 2265.98  5164.2 2274.43  5169.3 2274.48
    5185 2297.48  5195.2 2302.25  5328.4  2306.4  5523.1 2304.47  5703.5 2308.58
#Mann= 5 ,-1 , 0
  4530.8     .16       0  4869.9     .07       0    4976     .07       0
    4985     .07       0  5101.7     .16       0
Bank Sta=4976,4985
XS Rating Curve= 0 ,0
Exp/Cntr=0.3,0.1

Type RM Length L Ch R = 1 ,24367   ,134,134,134
BEGIN DESCRIPTION:
565
END DESCRIPTION:
XS GIS Cut Line= 3
      1509119.05      6790854.58      1508647.68      6790732.18
      1508048.03       6790719.2
#Sta/Elev= 30
    4521 2276.82  4597.5 2275.66  4659.5 2276.26  4731.8  2275.5    4767 2273.88
  4802.4 2259.05  4807.6 2258.67  4814.5 2255.57  4824.8 2253.52  4837.1 2252.38
  4924.1 2250.65  4938.5 2245.99  4990.1 2243.35  4995.5 2239.95    4996 2239.45
  5004.5 2239.95  5009.9 2240.54  5011.8 2240.54  5020.7 2244.69  5030.7 2246.38
  5080.7 2248.15  5140.7 2252.12  5150.7 2253.65  5170.7 2260.78  5230.7 2287.51
  5260.7 2290.43  5300.8 2297.59  5440.8 2304.55  5480.8 2307.26  5607.8 2311.39
#Mann= 5 ,-1 , 0
    4521     .16       0  4837.1     .07       0  4995.5     .07       0
  5004.5     .07       0  5009.9     .16       0
Bank Sta=4995.5,5004.5
XS Rating Curve= 0 ,0
Exp/Cntr=0.3,0.1

Type RM Length L Ch R = 1 ,24233   ,234,234,234
BEGIN DESCRIPTION:
563
END DESCRIPTION:
XS GIS Cut Line= 3
      1509095.64      6790768.65      1508652.89      6790599.37
      1508079.95      6790607.18
#Sta/Elev= 30
  4529.3 2274.56  4669.2  2274.8  4701.3 2273.39  4721.6 2270.23  4776.2 2254.59
  4794.7 2252.02  4872.6 2250.74    4894 2242.83  4909.6 2242.19  4958.2 2243.84
  4973.1 2239.78    4975  2239.3  4975.5  2238.8  4984.2  2239.3  5021.2 2246.07
  5091.2 2247.97  5101.2 2250.41  5111.2 2255.71  5121.2 2264.06  5131.2  2269.4
  5141.2 2271.99  5151.2 2271.51  5171.2 2266.84  5181.2 2267.57  5201.2 2273.89
  5211.2  2282.2  5221.2 2287.74    5268 2290.08  5301.2 2298.14  5576.3 2311.12
#Mann= 5 ,-1 , 0
  4529.3     .16       0  4721.6     .07       0  4973.1     .16       0
    4975     .07       0  4984.2     .16       0
Bank Sta=4975,4984.2
XS Rating Curve= 0 ,0
Exp/Cntr=0.3,0.1

Type RM Length L Ch R = 1 ,23999   ,156,156,156
BEGIN DESCRIPTION:
562
END DESCRIPTION:
XS GIS Cut Line= 3
      1509158.11      6790779.07      1508832.57      6790461.35
      1508226.35       6790242.8
#Sta/Elev= 30
  4544.4 2273.85  4639.3 2273.63  4722.7 2268.68  4745.3 2266.77  4752.4 2268.51
  4759.4 2266.68  4766.6 2267.86  4773.6 2265.41  4780.7 2266.26  4787.7 2263.85
  4844.3 2254.73  4929.2 2246.11  4950.5 2239.02  4964.6    2238  4981.2 2234.01
  4981.7 2233.51  4990.4 2234.01  5028.9 2241.77  5071.1 2244.74    5168 2244.54
  5197.1  2245.5  5209.3 2248.69  5219.9 2253.13  5251.8 2272.16  5258.5 2278.18
  5273.1 2283.86  5375.9 2288.88  5381.2 2287.72  5462.6 2297.02  5643.7 2306.31
#Mann= 5 ,-1 , 0
  4544.4     .16       0  4722.7     .07       0  4981.2     .07       0
  4990.4     .07       0    5168     .16       0
Bank Sta=4981.2,4990.4
XS Rating Curve= 0 ,0
Exp/Cntr=0.3,0.1

Type RM Length L Ch R = 1 ,23843   ,226,226,226
BEGIN DESCRIPTION:
561
END DESCRIPTION:
XS GIS Cut Line= 3
      1509184.15      6790724.38      1508934.14      6790362.39
      1508415.88      6790117.58
#Sta/Elev= 30
  4558.4 2268.36  4583.8 2272.54  4649.4 2273.05  4683.2  2271.5  4691.3 2271.64
  4706.2 2268.15  4712.3 2269.05  4721.1 2266.59  4727.1 2267.99  4735.9 2265.58
    4742 2267.19  4756.9 2261.89    4763 2262.85  4792.7 2255.37  4857.8 2252.17
  4965.8 2243.97  4993.4 2232.57  4993.9 2232.07  5002.6 2232.57  5017.1 2239.06
  5062.7 2239.28  5113.7    2243  5174.2 2242.71  5210.3  2242.9  5227.6 2249.94
  5240.7 2258.25  5262.8 2269.23  5278.6 2271.48  5406.6 2272.96  5571.5  2286.5
#Mann= 5 ,-1 , 0
  4558.4     .16       0  4683.2     .07       0  4993.4     .07       0
  5002.6     .07       0  5174.2     .16       0
Bank Sta=4993.4,5002.6
XS Rating Curve= 0 ,0
Exp/Cntr=0.3,0.1

Type RM Length L Ch R = 1 ,23617   ,235,235,235
BEGIN DESCRIPTION:
560
END DESCRIPTION:
XS GIS Cut Line= 3
       1509449.8      6790206.14      1508996.64      6790161.87
      1508504.42      6790086.34
#Sta/Elev= 30
  4553.6 2294.24  4558.5 2294.24  4584.7 2288.39  4589.7 2289.39  4628.8 2283.17
  4658.9 2276.85    4679  2269.9  4686.4 2264.94  4699.1 2259.65  4729.2 2252.85
  4799.6 2246.73  4965.7 2242.91  4970.4 2242.72  4990.5 2233.92  4996.5 2232.59
    4997 2232.09  5006.3 2232.59  5007.2 2234.08  5012.3 2234.08  5020.7  2236.7
  5091.5 2239.45  5112.6 2239.07  5142.1 2238.53  5152.2 2240.79  5198.5 2261.09
  5203.6  2264.9    5223 2263.98  5243.3 2267.51    5304  2271.2  5506.9 2276.41
#Mann= 5 ,-1 , 0
  4553.6     .16       0  4965.7     .07       0  4996.5     .07       0
  5006.3     .07       0  5112.6     .16       0
Bank Sta=4996.5,5006.3
XS Rating Curve= 0 ,0
Exp/Cntr=0.3,0.1

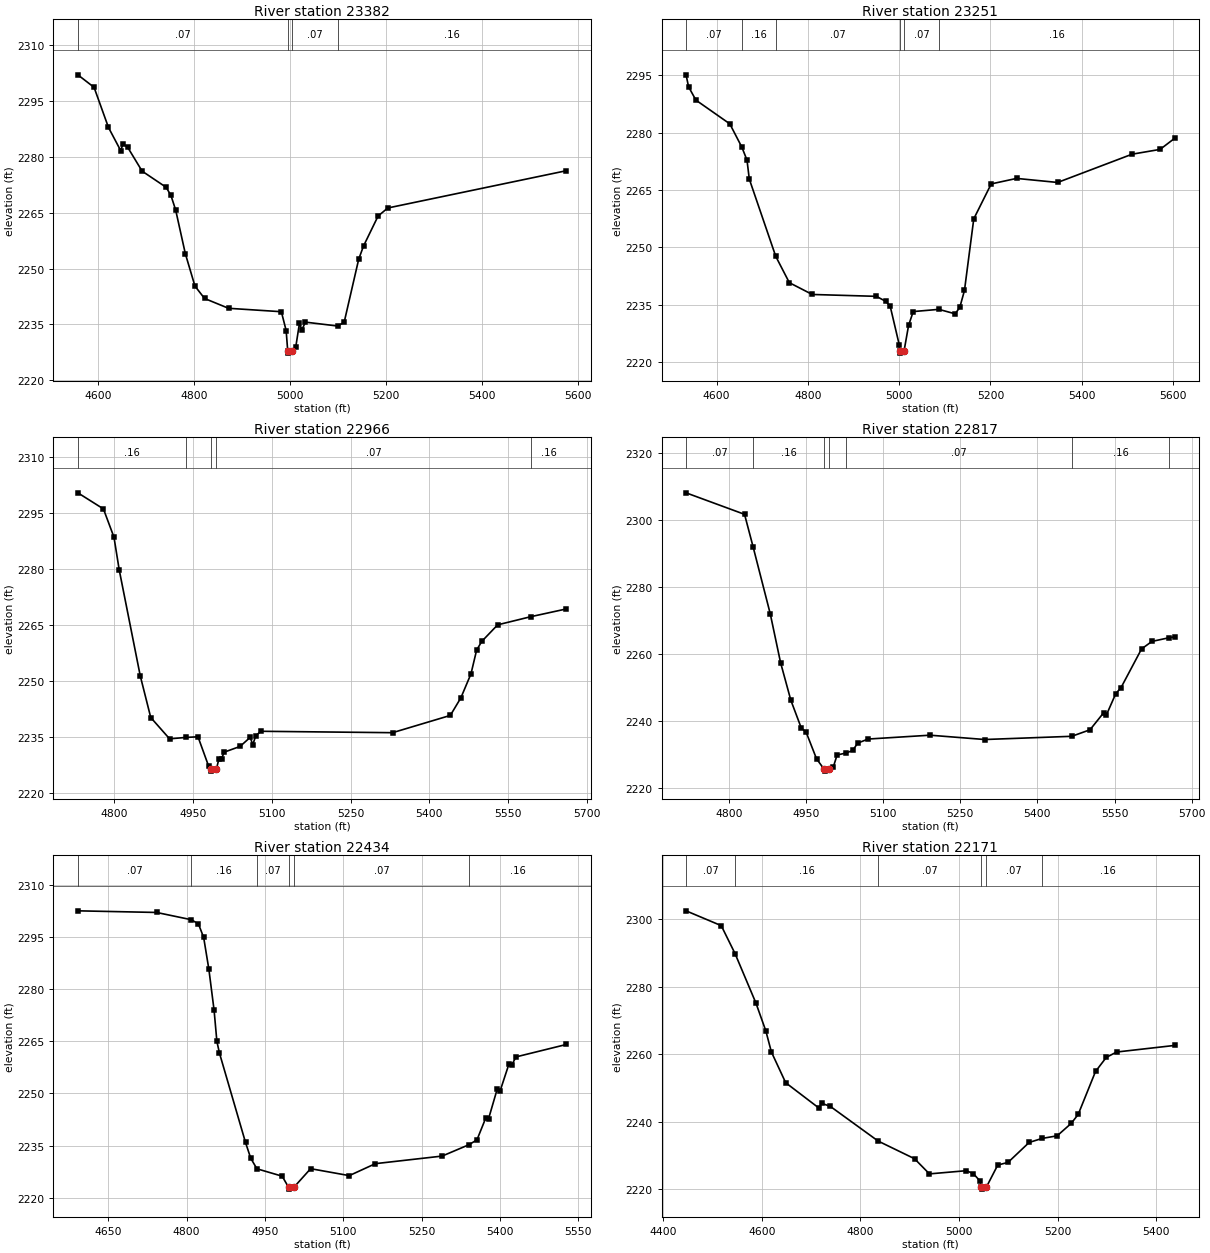
Type RM Length L Ch R = 1 ,23382   ,131,131,131
BEGIN DESCRIPTION:
559
END DESCRIPTION:
XS GIS Cut Line= 3
       1509488.8      6789956.14      1509043.51      6789940.51
      1508475.78      6790016.04
#Sta/Elev= 30
  4557.1 2302.02  4590.9 2298.66  4620.9 2287.89  4646.3 2281.69  4651.3 2283.45
    4661 2282.55    4691 2276.16    4741 2271.83    4751 2269.67    4761 2265.69
    4781 2254.04  4801.1  2245.3  4821.1 2241.97  4871.1 2239.33  4981.2 2238.41
  4991.2 2233.35  4994.5 2227.79    4995 2227.29  5004.3 2227.79  5011.3 2229.01
  5018.9 2235.28    5024 2233.58  5031.4 2235.61  5098.4 2234.57  5112.1 2235.58
  5142.4 2252.52  5152.5 2256.07  5182.8  2264.1  5202.9 2266.26  5575.4 2276.28
#Mann= 4 ,-1 , 0
  4557.1     .07       0  4994.5     .07       0  5004.3     .07       0
  5098.4     .16       0
Bank Sta=4994.5,5004.3
XS Rating Curve= 0 ,0
Exp/Cntr=0.3,0.1

Type RM Length L Ch R = 1 ,23251   ,285,285,285
BEGIN DESCRIPTION:
557
END DESCRIPTION:
XS GIS Cut Line= 3
      1509470.57      6789864.99      1508999.24      6789823.33
      1508413.62      6789943.05
#Sta/Elev= 30
    4533 2295.12  4538.6 2291.98  4554.6 2288.51  4628.9 2282.31  4655.3 2276.22
  4666.6 2272.83  4671.6 2267.89  4729.6 2247.68  4759.4  2240.8  4809.6 2237.72
  4950.2 2237.23  4970.3 2235.94  4980.3 2234.71  5000.4  2224.5  5000.9 2222.89
  5001.4 2222.39  5010.7 2222.89  5020.7 2229.63  5030.9 2233.25    5087 2233.83
  5122.8 2232.66    5133 2234.36  5143.2 2238.77  5163.6 2257.49  5201.8 2266.61
  5257.4 2268.05  5347.3 2266.99  5510.6 2274.38  5571.9 2275.63  5603.9 2278.54
#Mann= 6 ,-1 , 0
    4533     .07       0  4655.3     .16       0  4729.6     .07       0
  5000.9     .07       0  5010.7     .07       0    5087     .16       0
Bank Sta=5000.9,5010.7
XS Rating Curve= 0 ,0
Exp/Cntr=0.3,0.1

Type RM Length L Ch R = 1 ,22966   ,149,149,149
BEGIN DESCRIPTION:
558
END DESCRIPTION:
XS GIS Cut Line= 3
      1509423.73      6789628.01      1509150.28       6789620.2
      1508494.08      6789651.45
#Sta/Elev= 30
  4730.6 2300.51  4779.3 2296.19  4799.4 2288.59  4809.4  2279.8  4849.4 2251.39
  4869.4 2240.18  4905.3 2234.45  4936.4 2234.83  4959.4    2235  4979.4 2227.21
  4984.5 2226.28    4985 2225.78  4994.4 2226.28  4999.3 2229.14  5004.2 2229.14
  5009.4 2230.88  5039.5 2232.41  5058.7 2234.84  5063.8 2232.89  5069.5 2235.34
  5079.5 2236.48  5329.8  2236.1  5439.9 2240.74    5460 2245.47  5479.2  2251.9
    5490  2258.3    5500 2260.65    5530 2265.06  5593.1 2267.25  5661.1 2269.34
#Mann= 5 ,-1 , 0
  4730.6     .16       0  4936.4     .07       0  4984.5     .07       0
  4994.4     .07       0  5593.1     .16       0
Bank Sta=4984.5,4994.4
XS Rating Curve= 0 ,0
Exp/Cntr=0.3,0.1

Type RM Length L Ch R = 1 ,22817   ,383,383,383
BEGIN DESCRIPTION:
556
END DESCRIPTION:
XS GIS Cut Line= 3
       1509488.8      6789489.99      1509204.97      6789487.39
      1508540.88      6789544.68
#Sta/Elev= 30
  4716.6 2308.14  4830.4 2301.71  4847.2 2291.89  4880.4 2271.97  4900.4 2257.42
  4920.4 2246.15  4940.4 2237.97  4950.4  2236.5  4970.4 2228.63  4985.5 2225.45
    4986 2224.95  4995.4 2225.45  5002.9 2226.13  5010.4 2229.77  5028.1 2230.38
  5040.6 2231.12  5050.6 2233.33  5070.7 2234.54  5191.1 2235.69  5297.5  2234.4
  5466.8 2235.36  5502.3 2237.31  5529.2 2242.47  5534.2 2241.75  5552.5 2248.14
  5562.5 2249.87  5602.6 2261.48  5622.7 2263.72  5656.2 2264.83    5667 2265.09
#Mann= 7 ,-1 , 0
  4716.6     .07       0  4847.2     .16       0  4985.5     .07       0
  4995.4     .16       0  5028.1     .07       0  5466.8     .16       0
  5656.2     .07       0
Bank Sta=4985.5,4995.4
XS Rating Curve= 0 ,0
Exp/Cntr=0.3,0.1

Type RM Length L Ch R = 1 ,22434   ,263,263,263
BEGIN DESCRIPTION:
555
END DESCRIPTION:
XS GIS Cut Line= 3
      1509405.46      6789159.26      1509001.85       6789180.1
      1508528.96      6789421.74
#Sta/Elev= 30
    4592 2302.62  4742.7 2302.15  4809.4 2300.05  4822.8 2298.83  4832.8 2294.95
  4842.8 2285.75  4852.8 2273.91  4858.1 2264.98  4863.1  2261.6  4912.9 2235.89
  4922.9 2231.34  4934.7 2228.31    4983 2226.18  4995.4 2222.95  4995.9 2222.45
  5005.3 2222.95  5037.5 2228.34  5111.5 2226.34  5161.5 2229.79  5289.2 2231.97
  5340.8 2235.26  5355.9 2236.66  5372.5 2242.87  5378.1 2242.74  5394.7 2251.31
  5400.3  2250.8  5416.9 2258.41  5422.5 2258.24  5430.6 2260.54  5527.2 2264.13
#Mann= 6 ,-1 , 0
    4592     .07       0  4809.4     .16       0  4934.7     .07       0
  4995.4     .07       0  5005.3     .07       0  5340.8     .16       0
Bank Sta=4995.4,5005.3
XS Rating Curve= 0 ,0
Exp/Cntr=0.3,0.1

Type RM Length L Ch R = 1 ,22171   ,162,162,162
BEGIN DESCRIPTION:
554
END DESCRIPTION:
XS GIS Cut Line= 3
      1509356.02      6788966.55      1508796.12      6789021.24
      1508512.23      6789341.59
#Sta/Elev= 30
  4446.6 2302.57    4518 2298.17    4546 2289.87  4588.3 2275.21  4608.4 2266.93
  4619.6 2260.72  4648.6 2251.59  4716.3 2244.04  4721.3 2245.49    4739 2244.58
  4836.1 2234.28  4909.8 2229.05    4940 2224.55  5014.9  2225.5  5029.2  2224.6
  5043.4  2222.3  5045.1 2220.53  5045.6 2220.03  5055.1 2220.53  5078.5 2227.17
  5099.4 2227.96  5142.1 2233.87  5168.2 2235.06  5198.9 2235.84  5227.4 2239.52
  5241.6 2242.19  5276.7 2254.92  5298.5 2259.09  5319.4 2260.69  5437.2 2262.65
#Mann= 6 ,-1 , 0
  4446.6     .07       0    4546     .16       0  4836.1     .07       0
  5045.1     .07       0  5055.1     .07       0  5168.2     .16       0
Bank Sta=5045.1,5055.1
XS Rating Curve= 0 ,0
Exp/Cntr=0.3,0.1

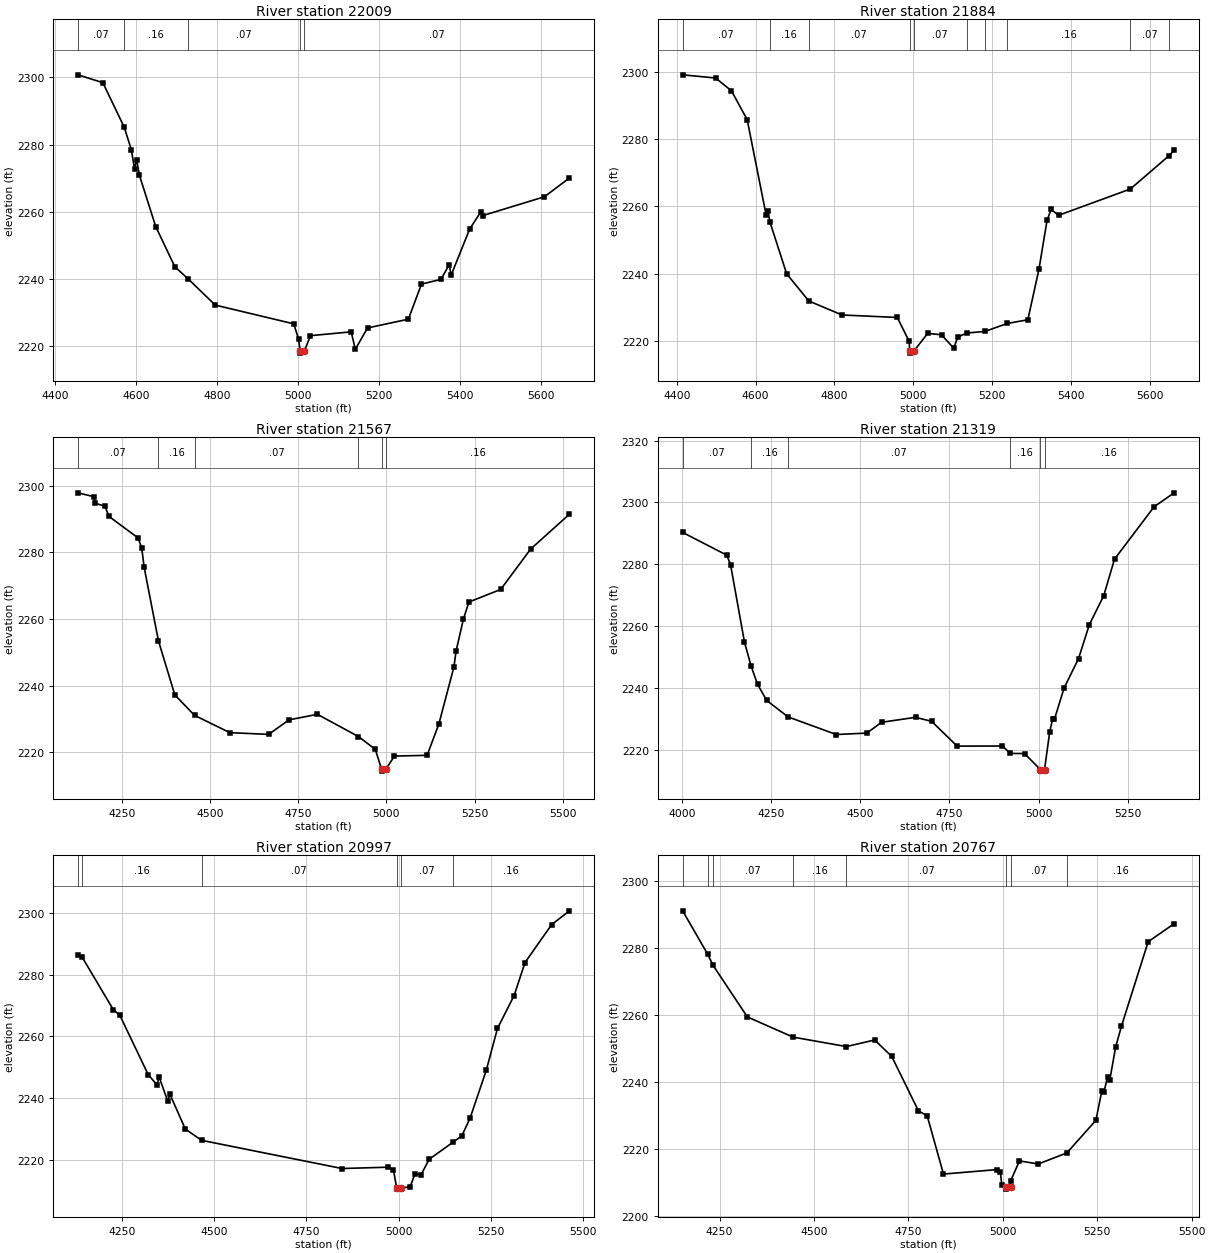
Type RM Length L Ch R = 1 ,22009   ,125,125,125
BEGIN DESCRIPTION:
553
END DESCRIPTION:
XS GIS Cut Line= 3
      1509296.09      6788927.49      1508759.66      6788872.81
       1508090.4      6788961.35
#Sta/Elev= 30
  4456.4 2300.71  4517.8 2298.38  4570.6 2285.15  4588.2 2278.45  4596.2  2272.7
  4601.3  2275.5  4608.3 2270.82  4648.5 2255.61  4695.8 2243.66  4728.9 2240.04
  4795.4  2232.3  4989.4 2226.72  5001.2 2222.29  5005.4 2218.52  5005.9 2218.02
  5015.4 2218.52  5030.6 2223.21  5131.4 2224.34  5141.5 2219.16  5171.8  2225.5
  5272.7 2228.11    5305 2238.53  5353.4 2239.94  5373.4 2244.28  5378.5 2241.22
    5424 2254.86  5451.9 2260.05  5456.9  2258.9  5608.8 2264.48  5670.7 2270.08
#Mann= 5 ,-1 , 0
  4456.4     .07       0  4570.6     .16       0  4728.9     .07       0
  5005.4     .07       0  5015.4     .07       0
Bank Sta=5005.4,5015.4
XS Rating Curve= 0 ,0
Exp/Cntr=0.3,0.1

Type RM Length L Ch R = 1 ,21884   ,317,317,317
BEGIN DESCRIPTION:
551
END DESCRIPTION:
XS GIS Cut Line= 3
      1509288.28       6788810.3      1508707.57      6788763.43
      1508061.72      6788922.29
#Sta/Elev= 30
  4414.6 2299.03  4498.1 2298.09  4538.3 2294.31  4578.4 2285.75  4626.6 2257.42
  4631.6 2258.62  4635.9 2255.44  4678.7 2239.93  4734.9 2231.86  4819.2  2227.7
  4959.6 2226.96  4989.7 2219.85    4991 2216.87  4991.5 2216.37    5001 2216.87
  5036.6 2222.23  5071.9 2221.82  5102.8 2217.83  5113.1 2221.14  5136.1 2222.34
  5182.3 2222.82  5238.7 2225.18  5290.9 2226.27  5319.1 2241.23  5339.7 2255.79
    5350 2259.06  5368.8  2257.3  5551.3 2265.12  5649.2 2274.99  5662.3 2276.66
#Mann= 10 ,-1 , 0
  4414.6     .07       0  4635.9     .16       0  4734.9     .07       0
    4991     .07       0    5001     .07       0  5136.1     .16       0
  5182.3     .07       0  5238.7     .16       0  5551.3     .07       0
  5649.2     .16       0
Bank Sta=4991,5001
XS Rating Curve= 0 ,0
Exp/Cntr=0.3,0.1

Type RM Length L Ch R = 1 ,21567   ,248,248,248
BEGIN DESCRIPTION:
552
END DESCRIPTION:
XS GIS Cut Line= 3
      1509288.27      6788786.86      1508621.64      6788588.95
      1507941.95      6788747.81
#Sta/Elev= 30
  4125.6  2297.9  4169.9 2296.75  4175.1 2294.76    4202 2293.86  4213.6  2290.8
  4295.9 2284.37  4306.3 2281.35  4313.2 2275.54  4353.6 2253.49  4400.2 2237.24
    4456 2231.11  4556.1 2225.92  4666.2  2225.4  4723.6 2229.75  4804.3 2231.42
  4920.8 2224.74  4968.5  2220.9  4986.5 2214.87    4987 2214.37  4997.8 2214.87
  5022.9 2218.89  5115.4 2219.11  5148.8 2228.57  5191.3 2245.61  5197.5  2250.4
  5218.1 2259.95  5233.9 2265.13    5324  2268.9    5409 2281.03    5519  2291.5
#Mann= 6 ,-1 , 0
  4125.6     .07       0  4353.6     .16       0    4456     .07       0
  4920.8     .16       0  4986.5     .07       0  4997.8     .16       0
Bank Sta=4986.5,4997.8
XS Rating Curve= 0 ,0
Exp/Cntr=0.3,0.1

Type RM Length L Ch R = 1 ,21319   ,322,322,322
BEGIN DESCRIPTION:
550
END DESCRIPTION:
XS GIS Cut Line= 3
       1509251.8      6788750.39      1508379.45      6788448.33
      1507929.48       6788388.5
#Sta/Elev= 30
  4002.3 2290.27  4125.9 2282.93  4136.5 2279.89  4175.6 2254.78    4194 2247.12
  4212.1 2241.16  4237.9 2235.92  4297.7 2230.61  4432.8 2224.91  4518.3 2225.37
  4559.8 2228.87    4655 2230.47    4700 2229.17  4771.4 2221.16  4898.4 2221.19
  4920.1  2218.8  4960.2 2218.75    5005 2213.57  5005.5 2213.07  5016.3 2213.57
  5030.8 2225.73  5038.8 2229.89  5043.9 2229.78  5071.2 2239.98  5111.5 2249.44
  5141.8 2260.42  5182.2 2269.83  5212.4 2281.63  5323.4 2298.58  5379.4 2303.08
#Mann= 6 ,-1 , 0
  4002.3     .07       0    4194     .16       0  4297.7     .07       0
  4920.1     .16       0    5005     .07       0  5016.3     .16       0
Bank Sta=5005,5016.3
XS Rating Curve= 0 ,0
Exp/Cntr=0.3,0.1

Type RM Length L Ch R = 1 ,20997   ,230,230,230
BEGIN DESCRIPTION:
549
END DESCRIPTION:
XS GIS Cut Line= 3
      1509283.12      6788547.29      1508486.22      6788213.95
      1508072.15       6787997.8
#Sta/Elev= 30
  4131.6  2286.5  4142.9 2285.66  4227.1 2268.69  4244.9 2266.85  4321.7 2247.67
  4345.5 2244.32  4350.9 2246.99  4374.7 2239.06  4380.1 2241.43  4422.2 2230.05
  4466.3  2226.4  4846.4 2217.28  4970.8  2217.7  4985.9 2216.79  4994.3 2211.11
  4994.8 2210.61  5005.6 2211.11  5030.6 2211.25  5044.1 2215.51  5060.6 2215.25
  5082.6 2220.28  5146.1  2225.7    5171 2227.85  5193.1  2233.5  5237.2 2249.07
  5267.5 2262.61  5312.6 2273.25    5342 2283.91  5414.2 2296.19  5462.5 2300.65
#Mann= 6 ,-1 , 0
  4131.6     .07       0  4142.9     .16       0  4466.3     .07       0
  4994.3     .07       0  5005.6     .07       0  5146.1     .16       0
Bank Sta=4994.3,5005.6
XS Rating Curve= 0 ,0
Exp/Cntr=0.3,0.1

Type RM Length L Ch R = 1 ,20767   ,332,332,332
BEGIN DESCRIPTION:
548
END DESCRIPTION:
XS GIS Cut Line= 4
       1509332.6      6788476.99      1508762.28      6788140.05
      1508613.82      6788031.66      1508226.53      6787792.52
#Sta/Elev= 30
  4152.2 2291.18  4218.5 2278.22  4232.8 2274.89  4323.6 2259.48  4444.6 2253.45
  4585.8 2250.62  4660.5 2252.59  4705.8  2247.7  4776.6 2231.41  4799.8 2229.92
  4842.9 2212.53    4985 2213.87  4993.5 2213.14  4997.3 2209.19  5009.1 2208.53
  5009.6 2208.03  5020.5 2208.53  5020.7  2210.5  5044.1 2216.47    5094 2215.54
  5169.5 2218.84  5246.5 2228.59  5261.9 2237.23  5267.8 2237.03  5277.3 2241.53
  5283.2  2240.6  5298.6 2250.41    5314 2256.67  5384.9 2281.94  5453.6 2287.33
#Mann= 8 ,-1 , 0
  4152.2     .07       0  4218.5     .16       0  4232.8     .07       0
  4444.6     .16       0  4585.8     .07       0  5009.1     .07       0
  5020.5     .07       0  5169.5     .16       0
Bank Sta=5009.1,5020.5
XS Rating Curve= 0 ,0
Exp/Cntr=0.3,0.1

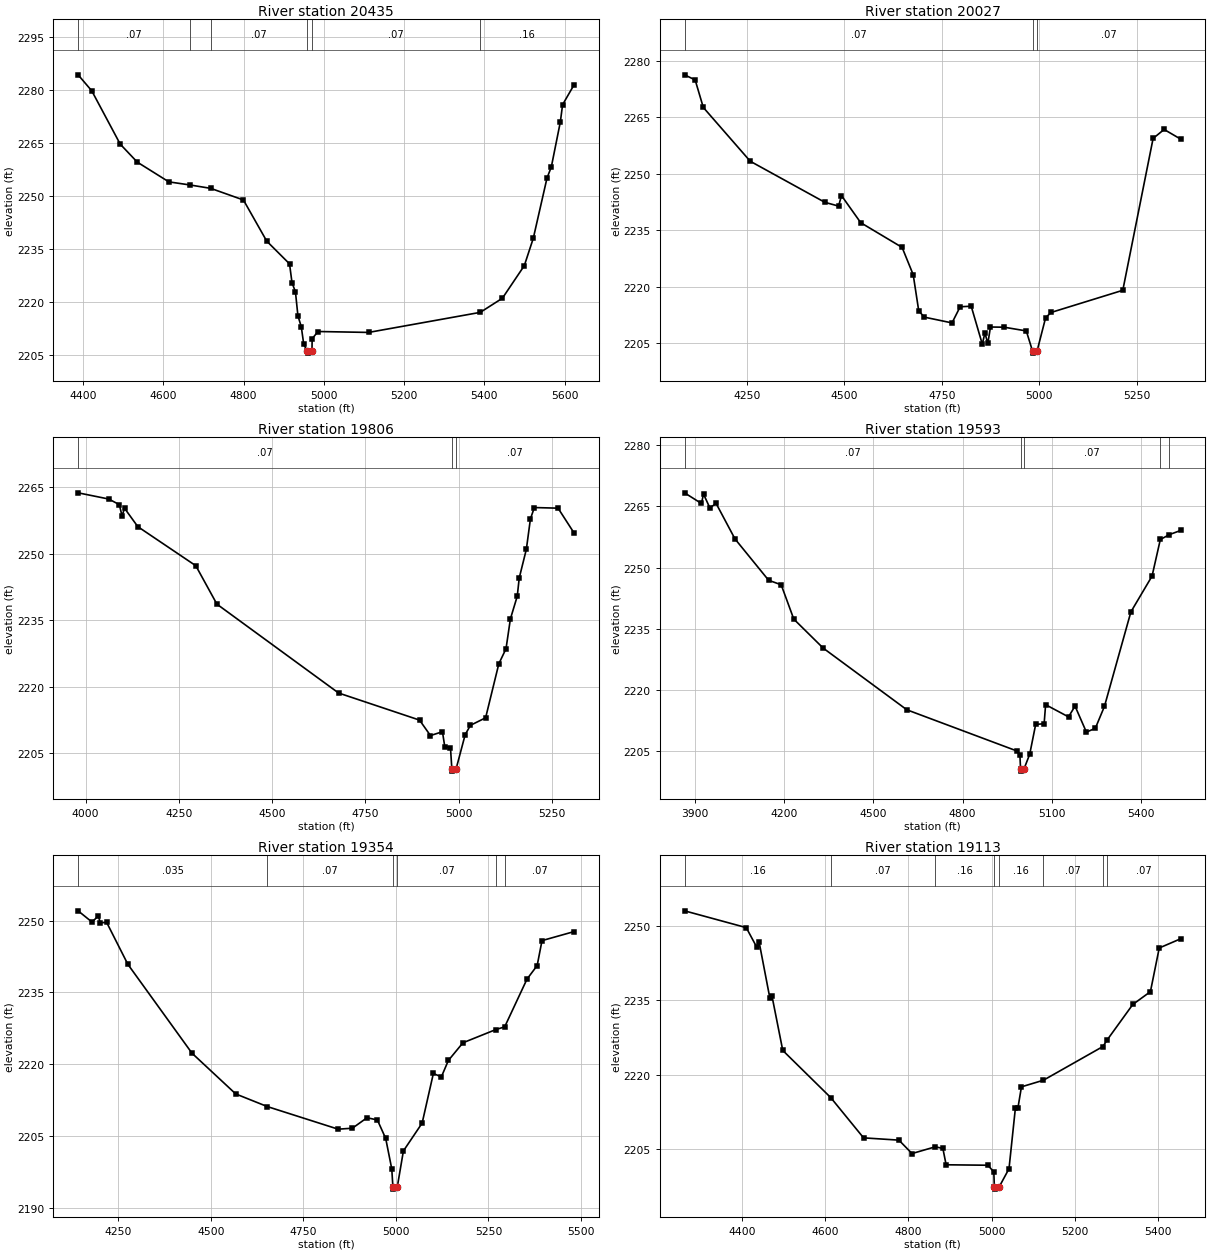
Type RM Length L Ch R = 1 ,20435   ,408,408,408
BEGIN DESCRIPTION:
544
END DESCRIPTION:
XS GIS Cut Line= 3
      1509363.81      6788385.81      1508871.64      6788023.85
      1508314.31      6787739.98
#Sta/Elev= 30
  4387.6 2284.29  4421.6 2279.78  4492.6  2264.7  4535.1 2259.62  4613.8 2254.04
  4665.5 2253.18    4718 2252.21  4799.7 2248.92  4857.8 2237.29  4914.6 2230.87
  4920.8 2225.52  4929.3 2222.99  4935.5 2216.19  4943.9  2213.1  4950.1 2208.08
  4959.1 2206.14  4959.6 2205.64  4970.5 2206.14    4971 2209.71  4985.6 2211.75
  5111.6 2211.49    5390 2217.16  5445.2 2221.16  5499.8 2230.37  5522.2 2238.11
  5556.4 2255.14  5567.1 2258.25  5589.6 2270.99  5595.2 2275.85    5624 2281.51
#Mann= 6 ,-1 , 0
  4387.6     .07       0  4665.5     .16       0    4718     .07       0
  4959.1     .07       0  4970.5     .07       0    5390     .16       0
Bank Sta=4959.1,4970.5
XS Rating Curve= 0 ,0
Exp/Cntr=0.3,0.1

Type RM Length L Ch R = 1 ,20027   ,221,221,221
BEGIN DESCRIPTION:
545
END DESCRIPTION:
XS GIS Cut Line= 3
      1509400.25      6788331.11      1508717.99      6787729.58
      1508460.79      6787472.38
#Sta/Elev= 30
  4089.6  2276.3  4116.8 2274.94  4137.7 2267.63  4258.2 2253.33  4449.8 2242.41
  4484.9 2241.41  4492.4  2244.2  4541.8    2237    4648 2230.43  4676.5 2223.17
  4690.7 2213.57  4704.9  2211.9  4776.1 2210.36    4797 2214.65  4825.4  2214.8
  4853.9  2204.7  4860.5 2207.69  4868.1 2204.92  4874.8 2209.27  4909.9 2209.22
  4966.8 2208.23  4982.9 2202.83  4983.4 2202.33  4994.3 2202.83  5016.5 2211.78
  5030.7 2213.15  5214.5 2219.03  5292.3  2259.4  5320.6 2261.78  5362.9 2259.22
#Mann= 3 ,-1 , 0
  4089.6     .07       0  4982.9     .07       0  4994.3     .07       0
Bank Sta=4982.9,4994.3
XS Rating Curve= 0 ,0
Exp/Cntr=0.3,0.1

Type RM Length L Ch R = 1 ,19806   ,213,213,213
BEGIN DESCRIPTION:
547
END DESCRIPTION:
XS GIS Cut Line= 4
      1509400.27      6788279.04      1509009.66      6787898.85
      1508832.57      6787549.89      1508465.39      6787409.27
#Sta/Elev= 30
    3980 2263.78  4062.2 2262.38  4090.5 2261.12  4097.7 2258.61  4104.7 2260.27
  4140.1 2256.15  4295.5 2247.34  4352.1 2238.67  4678.2 2218.63  4895.2 2212.52
  4924.5 2209.03  4956.6  2209.9  4962.8 2206.55  4978.1 2206.31  4981.8 2201.51
  4982.3 2201.01  4993.2 2201.51  5017.5 2209.23  5031.6 2211.34  5072.3 2213.04
  5107.7 2225.22    5127 2228.62  5138.7 2235.33  5157.1 2240.46  5162.4 2244.57
  5181.5 2251.05  5192.4 2257.89  5202.9 2260.46  5266.5 2260.32  5309.6 2254.69
#Mann= 3 ,-1 , 0
    3980     .07       0  4981.8     .07       0  4993.2     .07       0
Bank Sta=4981.8,4993.2
XS Rating Curve= 0 ,0
Exp/Cntr=0.3,0.1

Type RM Length L Ch R = 1 ,19593   ,239,239,239
BEGIN DESCRIPTION:
546
END DESCRIPTION:
XS GIS Cut Line= 4
       1509408.1      6788245.21      1509103.41      6787937.91
      1508777.89      6787312.91      1508723.27      6786782.35
#Sta/Elev= 30
  3863.7 2268.31  3920.5  2265.7  3927.6    2268  3948.8 2264.63    3970  2265.7
  4033.6 2257.01  4146.8 2246.89  4189.2 2245.78  4231.6 2237.37  4330.6 2230.27
  4612.3 2215.16  4984.1 2205.04  4993.2 2204.11  4995.4 2200.63  4995.9 2200.13
  5006.8 2200.63  5026.2 2204.26  5046.3 2211.57  5074.8 2211.75  5079.8 2216.41
  5156.9 2213.42  5178.9 2216.06  5217.2 2209.68  5247.3 2210.63    5278    2216
    5367 2239.14  5438.3 2247.91  5466.2 2256.88    5497 2258.08  5534.5 2259.09
#Mann= 5 ,-1 , 0
  3863.7     .07       0  4995.4     .07       0  5006.8     .07       0
  5466.2     .16       0    5497     .07       0
Bank Sta=4995.4,5006.8
XS Rating Curve= 0 ,0
Exp/Cntr=0.3,0.1

Type RM Length L Ch R = 1 ,19354   ,241,241,241
BEGIN DESCRIPTION:
543
END DESCRIPTION:
XS GIS Cut Line= 3
      1509345.59      6787958.73      1508967.99      6787187.91
       1508895.2      6786712.19
#Sta/Elev= 30
  4141.8 2252.08  4179.4 2249.73  4196.3 2251.01  4201.9 2249.55  4218.8 2249.68
  4276.2 2240.89  4449.4  2222.3  4567.5 2213.78  4652.7 2211.14  4844.1 2206.41
  4882.5 2206.61    4922  2208.8    4950 2208.34  4972.5 2204.47  4988.9 2198.09
  4991.9 2194.37  4992.4 2193.87  5003.9 2194.37  5020.3 2201.86  5070.9 2207.68
  5101.2 2218.06  5122.8 2217.34  5141.7 2220.78  5181.1 2224.48  5270.1 2227.25
  5293.8 2227.81  5354.1  2237.8  5381.5 2240.63  5394.6 2245.85  5481.4 2247.74
#Mann= 6 ,-1 , 0
  4141.8    .035       0  4652.7     .07       0  4991.9     .07       0
  5003.9     .07       0  5270.1     .16       0  5293.8     .07       0
Bank Sta=4991.9,5003.9
XS Rating Curve= 0 ,0
Exp/Cntr=0.3,0.1

Type RM Length L Ch R = 1 ,19113   ,355,355,355
BEGIN DESCRIPTION:
542
END DESCRIPTION:
XS GIS Cut Line= 3
      1509418.51      6787784.25      1509178.93      6787099.37
      1508929.49      6786704.42
#Sta/Elev= 30
  4261.7 2252.96    4410 2249.58  4435.7 2245.58    4441 2246.66  4466.7 2235.44
    4472 2235.76  4497.8 2224.86    4613 2215.38  4692.1 2207.26  4777.1  2206.8
  4808.6  2204.1  4864.6 2205.46  4882.8 2205.13  4890.6 2201.84    4991 2201.75
  5005.3  2200.4  5006.5 2197.44    5007 2196.94  5018.5 2197.44  5041.8 2201.05
  5057.1 2213.23    5063 2213.17  5071.7 2217.53  5124.5 2218.86  5267.5 2225.64
  5278.3 2227.03  5339.4 2234.11  5381.8 2236.69    5403 2245.48  5454.4 2247.33
#Mann= 8 ,-1 , 0
  4261.7     .16       0    4613     .07       0  4864.6     .16       0
  5006.5     .07       0  5018.5     .16       0  5124.5     .07       0
  5267.5     .16       0  5278.3     .07       0
Bank Sta=5006.5,5018.5
XS Rating Curve= 0 ,0
Exp/Cntr=0.3,0.1

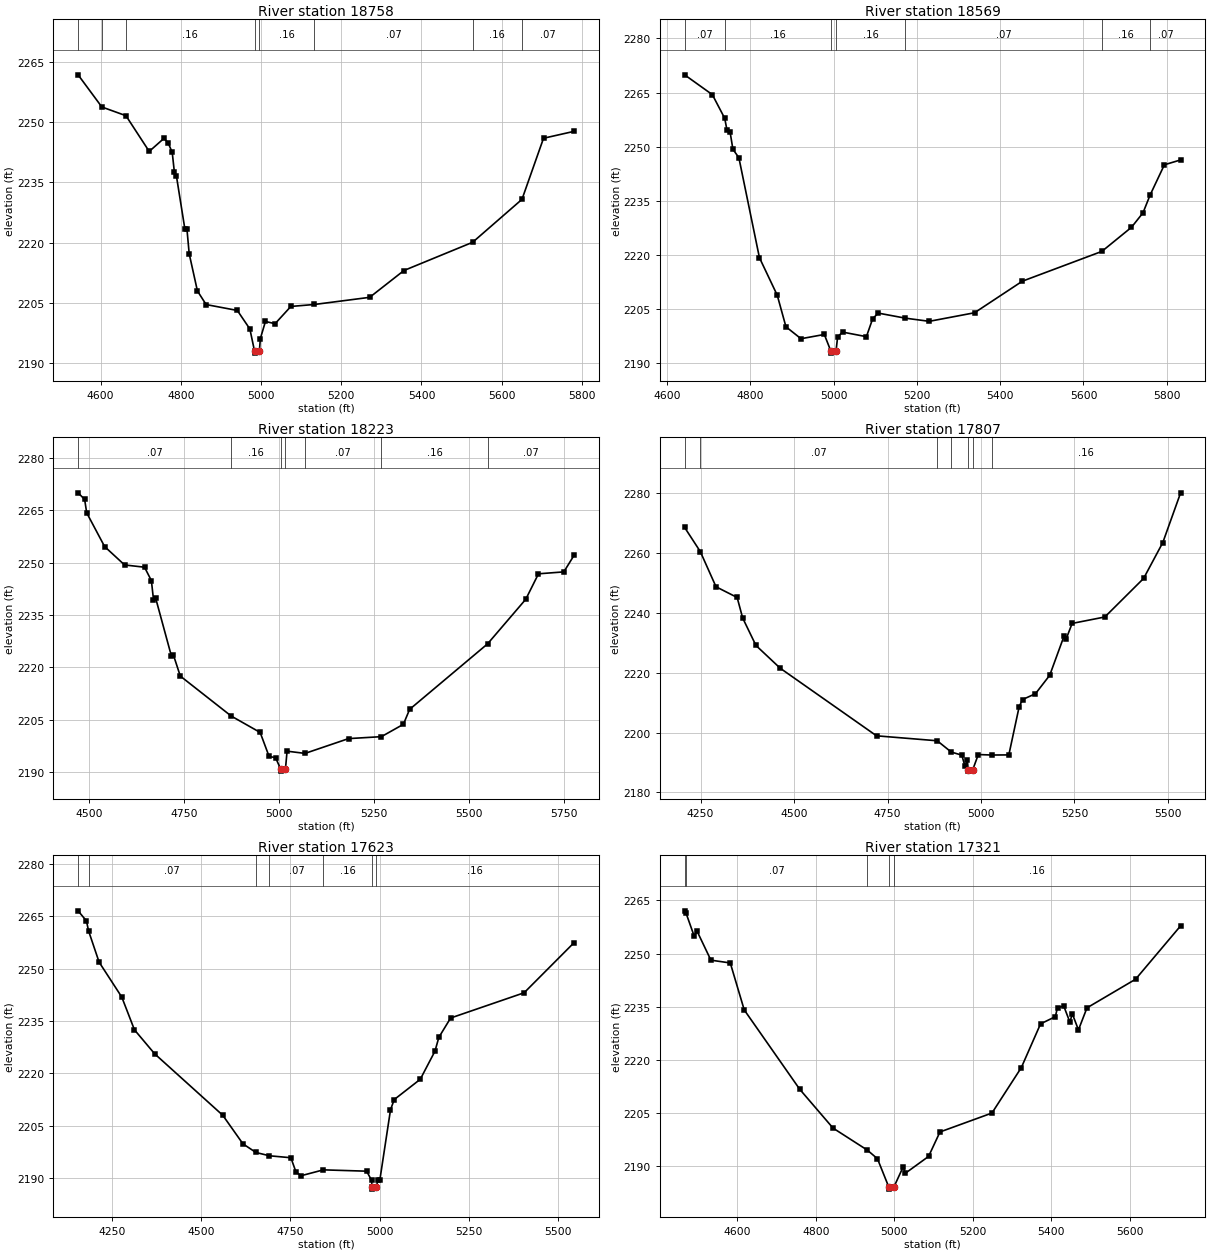
Type RM Length L Ch R = 1 ,18758   ,189,189,189
BEGIN DESCRIPTION:
541
END DESCRIPTION:
XS GIS Cut Line= 3
      1509637.28      6787620.24      1509457.57      6787091.56
       1508924.2      6786672.66
#Sta/Elev= 30
  4543.9 2261.78  4603.1 2253.77  4663.2  2251.6  4721.2  2242.7  4757.9 2245.94
  4768.1  2244.9  4778.6 2242.45    4784 2237.48  4789.2 2236.49  4810.1 2223.38
  4815.3 2223.33  4820.9 2217.21  4841.4 2207.94  4863.1 2204.55  4940.9 2203.08
  4972.2 2198.46  4983.8 2192.95  4984.3 2192.45  4995.9 2192.95  4998.3 2196.07
    5011 2200.34    5035 2199.78  5074.4 2204.08    5133 2204.57  5270.9 2206.35
  5356.3 2213.03  5527.5 2220.06  5650.6 2230.76  5704.3 2245.98  5780.5  2247.7
#Mann= 8 ,-1 , 0
  4543.9     .16       0  4603.1     .07       0  4663.2     .16       0
  4983.8     .07       0  4995.9     .16       0    5133     .07       0
  5527.5     .16       0  5650.6     .07       0
Bank Sta=4983.8,4995.9
XS Rating Curve= 0 ,0
Exp/Cntr=0.3,0.1

Type RM Length L Ch R = 1 ,18569   ,346,346,346
BEGIN DESCRIPTION:
540
END DESCRIPTION:
XS GIS Cut Line= 3
      1509895.08      6787401.46      1509655.49       6787120.2
      1508965.97      6786672.66
#Sta/Elev= 30
  4641.8 2269.92  4708.4 2264.43  4738.1 2257.88  4743.5 2254.66  4751.2 2253.96
  4757.8 2249.29  4772.1 2246.98  4821.5 2219.27  4864.3 2208.87  4885.2 2200.13
  4921.4 2196.82  4977.4    2198  4993.3 2193.33  4993.8 2192.83  5005.4 2193.33
  5009.4 2197.34  5021.2 2198.66  5078.5 2197.39  5093.7 2202.42  5107.2 2203.91
  5171.8 2202.52  5229.5 2201.64  5338.2 2204.01    5453 2212.75  5644.1 2221.01
  5715.2 2227.68  5742.9 2231.69    5760 2236.62  5794.3    2245  5833.3 2246.35
#Mann= 7 ,-1 , 0
  4641.8     .07       0  4738.1     .16       0  4993.3     .07       0
  5005.4     .16       0  5171.8     .07       0  5644.1     .16       0
    5760     .07       0
Bank Sta=4993.3,5005.4
XS Rating Curve= 0 ,0
Exp/Cntr=0.3,0.1

Type RM Length L Ch R = 1 ,18223   ,416,416,416
BEGIN DESCRIPTION:
539
END DESCRIPTION:
XS GIS Cut Line= 3
      1510142.46      6787021.24      1509668.51      6786818.12
      1508909.08      6786597.05
#Sta/Elev= 30
  4471.2 2270.01  4488.4 2268.14  4493.9 2264.27    4541 2254.62  4593.6 2249.34
  4646.2 2248.69  4664.3 2244.84  4669.8 2239.42  4675.2 2239.96  4716.9 2223.27
  4722.4  2223.5  4740.4 2217.49  4874.4 2206.04  4950.8 2201.33  4974.4 2194.44
  4991.3 2194.11  5005.3 2190.74  5005.8 2190.24  5017.4 2190.74  5021.7 2195.96
    5069 2195.32  5183.6 2199.56  5270.2 2200.12  5328.1 2203.66  5344.6 2207.95
  5549.9 2226.72  5650.5  2239.5    5684  2246.8  5750.8 2247.35  5777.8 2252.11
#Mann= 7 ,-1 , 0
  4471.2     .07       0  4874.4     .16       0  5005.3     .07       0
  5017.4     .16       0    5069     .07       0  5270.2     .16       0
  5549.9     .07       0
Bank Sta=5005.3,5017.4
XS Rating Curve= 0 ,0
Exp/Cntr=0.3,0.1

Type RM Length L Ch R = 1 ,17807   ,184,184,184
BEGIN DESCRIPTION:
538
END DESCRIPTION:
XS GIS Cut Line= 3
      1510145.06      6786914.46      1509504.45      6786450.93
      1509033.13      6786195.74
#Sta/Elev= 30
  4207.2 2268.54  4249.1 2260.48  4291.2 2248.71  4347.7 2245.14  4362.4  2238.3
    4398 2229.11  4462.9  2221.5  4720.5 2198.92  4882.9 2197.26  4920.4 2193.49
  4948.6 2192.46  4957.2 2188.73  4963.3 2190.79  4965.8 2187.62  4966.3 2187.12
    4978 2187.62  4992.7 2192.66  5029.4  2192.5  5074.4 2192.54    5102 2208.61
    5111 2211.03  5145.7 2212.99  5183.8 2219.15  5221.8 2232.14  5227.5  2231.2
  5243.7 2236.47  5331.2 2238.62  5434.9  2251.5  5486.3  2263.5  5533.9  2280.1
#Mann= 7 ,-1 , 0
  4207.2     .16       0  4249.1     .07       0  4882.9     .16       0
  4920.4     .07       0  4965.8     .07       0    4978     .07       0
  5029.4     .16       0
Bank Sta=4965.8,4978
XS Rating Curve= 0 ,0
Exp/Cntr=0.3,0.1

Type RM Length L Ch R = 1 ,17623   ,302,302,302
BEGIN DESCRIPTION:
537
END DESCRIPTION:
XS GIS Cut Line= 3
      1510139.89      6786896.27       1509535.7      6786310.31
      1509382.05      6785784.25
#Sta/Elev= 30
  4155.5 2266.53  4178.9 2263.64  4184.8  2260.8  4214.4 2251.83  4277.9 2241.83
  4313.4 2232.45    4370 2225.58  4560.9 2207.97  4617.4 2199.79  4653.7 2197.32
  4691.7 2196.37  4751.7 2195.81  4765.9 2191.74    4780 2190.65  4842.7 2192.34
  4963.9 2191.96  4978.1  2189.3  4978.9 2187.32  4979.4 2186.82  4991.2 2187.32
  4995.2 2189.45    5001 2189.45  5030.8 2209.52  5041.2 2212.47  5114.2 2218.28
  5155.4 2226.33  5166.3  2230.3  5199.3 2235.83  5405.2 2243.06  5545.2 2257.42
#Mann= 7 ,-1 , 0
  4155.5     .16       0  4184.8     .07       0  4653.7     .16       0
  4691.7     .07       0  4842.7     .16       0  4978.9     .07       0
  4991.2     .16       0
Bank Sta=4978.9,4991.2
XS Rating Curve= 0 ,0
Exp/Cntr=0.3,0.1

Type RM Length L Ch R = 1 ,17321   ,171,171,171
BEGIN DESCRIPTION:
536
END DESCRIPTION:
XS GIS Cut Line= 3
      1510184.13      6786763.42      1509801.32      6786385.83
      1509441.94      6785755.59
#Sta/Elev= 30
  4465.9 2262.07  4469.4 2261.46  4490.4 2254.89  4497.4 2256.38  4532.8 2248.15
  4582.2 2247.36  4617.7 2234.11  4759.1 2211.71  4843.9 2200.76  4931.2 2194.55
    4957 2192.12  4986.2 2184.04  4986.7 2183.54  4998.5 2184.04  5022.4 2189.79
  5028.2 2188.03  5087.2 2192.77  5116.2 2199.67  5248.6 2205.01  5323.4 2217.83
  5372.4 2230.18  5409.9 2232.19  5415.6 2234.74  5431.5 2235.19  5447.3 2230.61
  5453.1 2233.07  5468.9 2228.47  5490.6 2234.69  5614.4 2242.77  5729.1 2257.83
#Mann= 5 ,-1 , 0
  4465.9     .16       0  4469.4     .07       0  4931.2     .16       0
  4986.2     .07       0  4998.5     .16       0
Bank Sta=4986.2,4998.5
XS Rating Curve= 0 ,0
Exp/Cntr=0.3,0.1