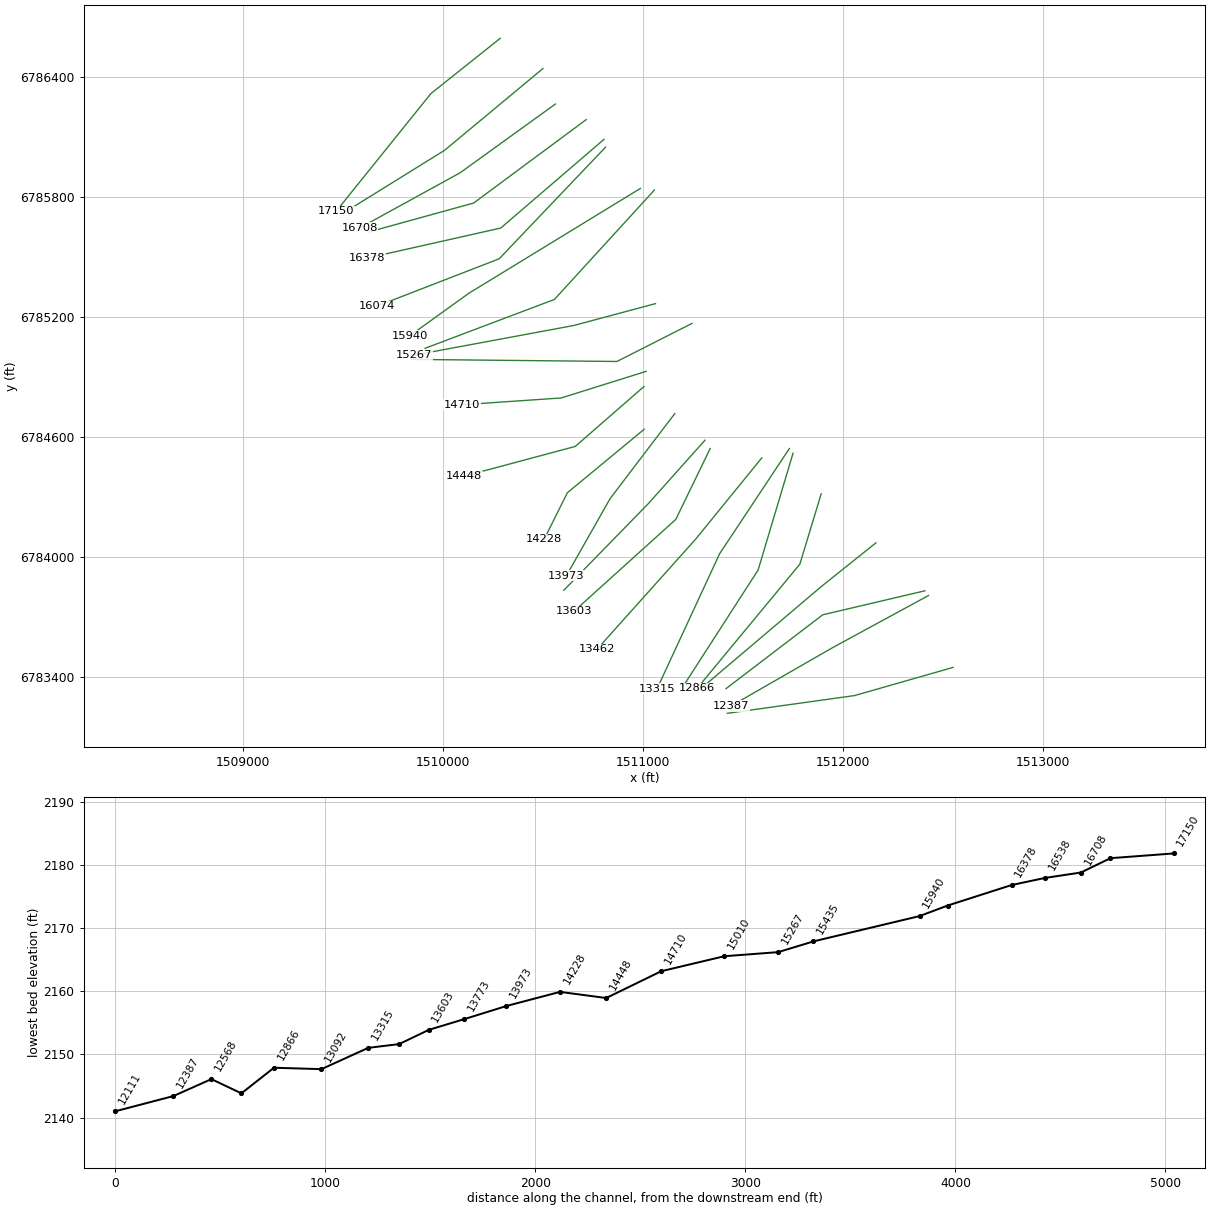
HEC-RAS study Cedar Creek 2.prj: Cedar Creek 2 Base Level Engineering

--- Cedar Creek 2.g01 (geometry) --- (continued)

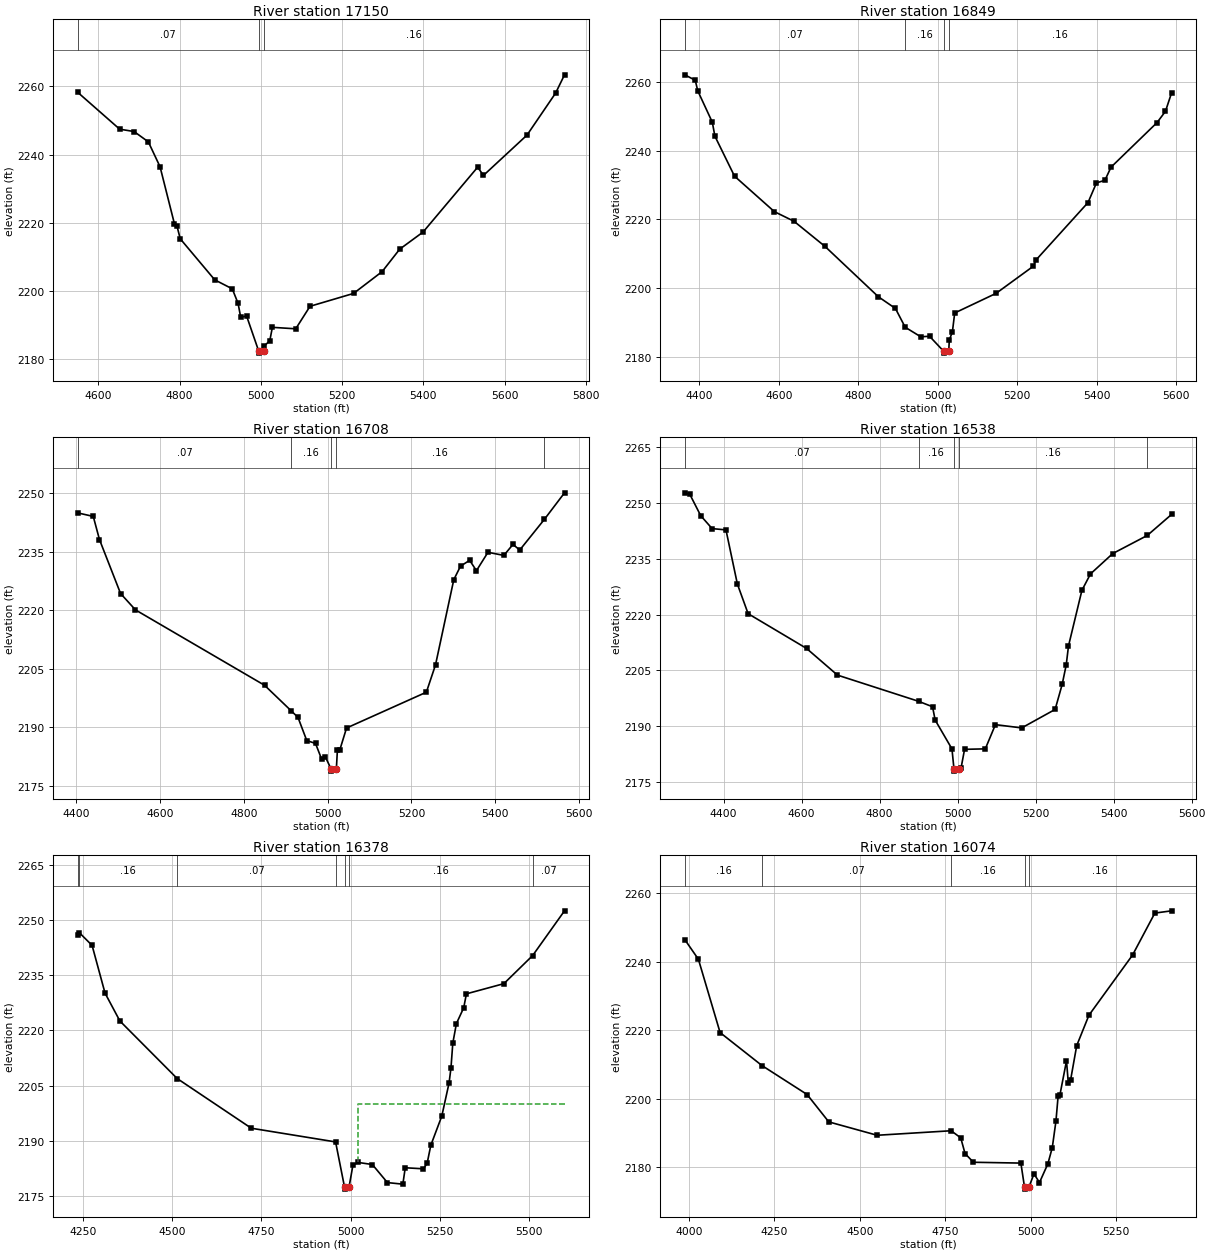
Type RM Length L Ch R = 1 ,17150   ,301,301,301
BEGIN DESCRIPTION:
535
END DESCRIPTION:
XS GIS Cut Line= 3
      1510285.69      6786591.55      1509939.35      6786315.51
      1509465.41      6785727.01
#Sta/Elev= 30
  4549.1 2258.24  4652.3 2247.45  4687.7 2246.76  4722.9 2243.73  4751.8 2236.41
    4787 2219.77  4793.4 2219.07  4801.4 2215.32  4886.3 2203.29  4929.5 2200.65
  4943.9 2196.38  4950.3 2192.29  4964.8  2192.7  4994.9  2182.3  4995.4  2181.8
  5007.2  2182.3  5007.5 2183.81  5021.9 2185.43  5028.3 2189.36  5085.8 2188.93
    5121 2195.53  5228.2  2199.3  5298.6  2205.7  5341.8 2212.27  5399.4  2217.3
  5533.7  2236.3  5548.1  2233.9  5655.3 2245.72  5725.7 2258.03  5747.6 2263.38
#Mann= 3 ,-1 , 0
  4549.1     .07       0  4994.9     .07       0  5007.2     .16       0
Bank Sta=4994.9,5007.2
XS Rating Curve= 0 ,0
Exp/Cntr=0.3,0.1

Type RM Length L Ch R = 1 ,16849   ,141,141,141
BEGIN DESCRIPTION:
534
END DESCRIPTION:
XS GIS Cut Line= 3
      1510499.23       6786440.5      1510007.05      6786031.66
      1509509.51      6785723.28
#Sta/Elev= 30
  4363.3 2262.09  4389.5 2260.51    4396  2257.4  4432.5 2248.29    4439 2244.23
  4488.4 2232.58  4588.7 2222.25  4638.2 2219.44  4716.3 2212.11  4850.4 2197.47
  4893.4 2194.06    4918 2188.59  4957.2 2185.81  4979.3 2185.96  5015.2 2181.55
  5015.7 2181.05  5027.5 2181.55  5029.1 2184.89  5036.8 2187.24  5042.6 2192.74
  5146.7 2198.45  5240.9 2206.39    5247 2208.14  5378.2  2224.9  5399.4 2230.62
  5420.7 2231.38  5436.1  2235.2  5551.8 2248.17  5573.1 2251.46  5588.5 2256.84
#Mann= 4 ,-1 , 0
  4363.3     .07       0    4918     .16       0  5015.2     .07       0
  5027.5     .16       0
Bank Sta=5015.2,5027.5
XS Rating Curve= 0 ,0
Exp/Cntr=0.3,0.1

Type RM Length L Ch R = 1 ,16708   ,170,170,170
BEGIN DESCRIPTION:
533
END DESCRIPTION:
XS GIS Cut Line= 3
      1510561.75      6786263.44      1510085.18      6785919.68
       1509582.6      6785643.65
#Sta/Elev= 30
    4404  2244.9    4441    2244  4455.8 2238.07  4506.1 2224.26  4541.6 2220.07
  4849.6 2200.76  4913.8 2194.15  4929.3 2192.54  4950.2 2186.61  4971.1 2185.87
  4985.8 2181.82  4994.6 2182.42  5008.5 2179.28    5009 2178.78  5020.8 2179.28
  5023.3 2184.18    5029  2184.2  5045.1 2189.82  5235.5 2198.99  5257.3 2205.98
  5300.9  2227.8    5317 2231.27  5338.8 2232.76  5354.9  2230.1  5382.4 2234.81
  5420.3 2234.02  5442.1 2236.83  5458.2 2235.39  5516.8 2243.22    5565 2250.04
#Mann= 5 ,-1 , 0
    4404     .07       0  4913.8     .16       0  5008.5     .07       0
  5020.8     .16       0  5516.8     .07       0
Bank Sta=5008.5,5020.8
XS Rating Curve= 0 ,0
Exp/Cntr=0.3,0.1

Type RM Length L Ch R = 1 ,16538   ,160,160,160
BEGIN DESCRIPTION:
532
END DESCRIPTION:
XS GIS Cut Line= 3
      1510715.42      6786185.33      1510152.89      6785768.64
      1509624.58       6785622.9
#Sta/Elev= 30
  4300.4 2252.77  4313.4 2252.33  4341.2 2246.62  4370.4 2243.15  4405.9  2242.8
  4435.2 2228.23  4462.7 2220.27  4612.5 2210.93  4691.8 2203.75  4899.7 2196.71
  4935.6 2195.24  4942.3 2191.66  4985.4  2183.9  4990.6 2178.43  4991.1 2177.93
    5003 2178.43  5008.6 2178.71  5017.7 2183.79  5070.9 2183.92  5096.8 2190.43
  5164.2 2189.55  5249.9 2194.52    5268 2201.26  5278.4 2206.52  5284.2  2211.6
  5318.6 2226.55  5340.6 2230.97  5397.7 2236.44  5486.1  2241.3  5548.5 2246.96
#Mann= 5 ,-1 , 0
  4300.4     .07       0  4899.7     .16       0  4990.6     .07       0
    5003     .16       0  5486.1     .07       0
Bank Sta=4990.6,5003
XS Rating Curve= 0 ,0
Exp/Cntr=0.3,0.1

Type RM Length L Ch R = 1 ,16378   ,304,304,304
BEGIN DESCRIPTION:
531
END DESCRIPTION:
XS GIS Cut Line= 3
       1510803.9      6786086.32       1510288.3      6785643.64
      1509619.07      6785493.19
#Sta/Elev= 30
  4234.8 2246.01  4239.5 2246.59    4275 2243.16  4311.3 2230.17    4353 2222.58
  4513.7 2206.91  4721.7 2193.38  4958.1 2189.65  4983.3  2177.3  4983.8  2176.8
  4995.7  2177.3  5006.7 2183.29  5020.3 2184.08  5061.2  2183.5  5103.5 2178.58
  5146.8 2178.15  5153.5 2182.62  5204.7 2182.33    5215 2183.86  5225.2 2188.73
    5256 2196.67  5276.5 2205.73  5281.8 2209.82  5286.9 2216.52    5297 2221.87
  5317.5 2226.17  5325.1 2229.97  5430.2 2232.74  5510.9 2240.39  5600.3 2252.57
#Mann= 7 ,-1 , 0
  4234.8     .07       0  4239.5     .16       0  4513.7     .07       0
  4958.1     .16       0  4983.3     .07       0  4995.7     .16       0
  5510.9     .07       0
#XS Ineff= 2 , 0
       0                    5020       0    2200
Permanent Ineff=
       F       F
Bank Sta=4983.3,4995.7
XS Rating Curve= 0 ,0
Exp/Cntr=0.3,0.1

Type RM Length L Ch R = 1 ,16074   ,134,134,134
BEGIN DESCRIPTION:
530
END DESCRIPTION:
XS GIS Cut Line= 3
      1510811.77      6786047.31      1510280.49      6785489.99
      1509669.29      6785253.32
#Sta/Elev= 30
  3987.6 2246.47  4027.4 2240.73  4090.9 2219.31  4213.7 2209.66  4345.7 2201.21
  4409.2 2193.21  4550.8  2189.3  4767.5 2190.62  4795.6 2188.54  4808.2 2183.96
  4832.7 2181.41  4971.7 2181.17  4982.5 2174.06    4983 2173.56  4994.9 2174.06
  5010.1 2178.01  5026.2 2175.49  5050.8 2180.97  5063.7 2185.72  5074.4 2193.43
  5080.7 2200.68    5086 2201.07  5105.3 2211.06  5110.6 2204.53  5117.3 2205.45
  5135.2  2215.5    5171 2224.38  5298.7 2241.96    5364 2254.23    5413 2254.89
#Mann= 5 ,-1 , 0
  3987.6     .16       0  4213.7     .07       0  4767.5     .16       0
  4982.5     .07       0  4994.9     .16       0
Bank Sta=4982.5,4994.9
XS Rating Curve= 0 ,0
Exp/Cntr=0.3,0.1

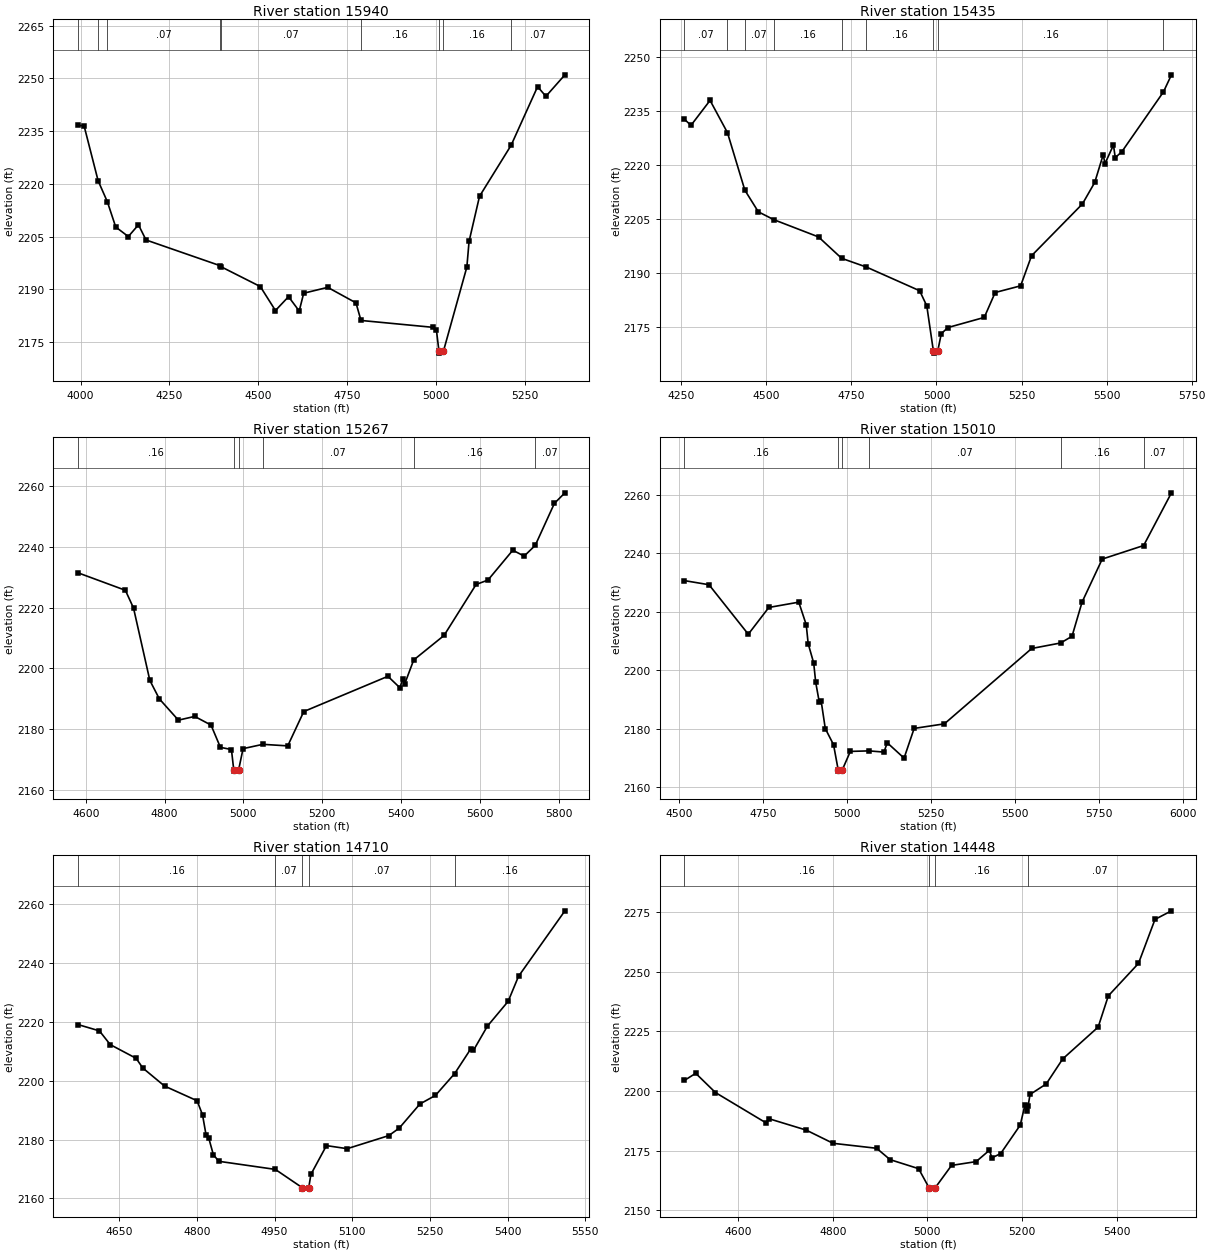
Type RM Length L Ch R = 1 ,15940   ,505,505,505
BEGIN DESCRIPTION:
529
END DESCRIPTION:
XS GIS Cut Line= 3
      1510986.25      6785841.57      1510129.45      6785318.12
      1509832.61       6785104.6
#Sta/Elev= 30
  3992.1 2236.64  4009.8 2236.52  4049.3  2220.9  4075.4 2214.89  4098.8 2207.75
  4134.2 2205.03  4162.7 2208.37    4184 2204.06  4391.5 2196.78    4396  2196.4
  4505.3 2190.82  4547.9    2184  4584.7 2187.94  4614.7 2183.86  4627.3 2188.92
  4694.9 2190.59  4774.3 2186.18  4788.4 2181.18  4991.1 2179.22  5000.5 2178.44
  5007.7 2172.39  5008.2 2171.89  5020.1 2172.39  5086.1 2196.36  5092.3 2203.66
  5121.7 2216.48  5210.5 2230.97    5285 2247.65  5308.3  2244.9  5361.8 2251.01
#Mann= 9 ,-1 , 0
  3992.1     .07       0  4049.3     .16       0  4075.4     .07       0
  4391.5     .16       0    4396     .07       0  4788.4     .16       0
  5007.7     .07       0  5020.1     .16       0  5210.5     .07       0
Bank Sta=5007.7,5020.1
XS Rating Curve= 0 ,0
Exp/Cntr=0.3,0.1

Type RM Length L Ch R = 1 ,15435   ,168,168,168
BEGIN DESCRIPTION:
528
END DESCRIPTION:
XS GIS Cut Line= 3
      1511056.55      6785833.76      1510556.53      6785286.87
      1509910.27       6785042.9
#Sta/Elev= 30
  4258.8 2232.76  4278.4 2231.05  4334.5 2237.97  4385.6 2229.03  4436.7 2213.08
  4476.3 2207.08  4521.7  2204.9  4653.3 2200.11  4721.2 2194.18  4793.9 2191.76
  4950.5 2185.19  4971.5 2180.99    4991 2168.39  4991.5 2167.89  5003.5 2168.39
  5014.1 2173.28  5033.5 2174.98  5140.4 2177.79  5172.5  2184.7  5247.3 2186.55
  5279.4 2194.89    5429 2209.27  5465.1 2215.22    5490 2222.91  5495.3 2220.45
  5520.1 2225.58  5525.5 2222.09    5545 2223.77  5667.1 2240.33  5690.6 2245.06
#Mann= 9 ,-1 , 0
  4258.8     .07       0  4385.6     .16       0  4436.7     .07       0
  4521.7     .16       0  4721.2     .07       0  4793.9     .16       0
    4991     .07       0  5003.5     .16       0  5667.1     .07       0
Bank Sta=4991,5003.5
XS Rating Curve= 0 ,0
Exp/Cntr=0.3,0.1

Type RM Length L Ch R = 1 ,15267   ,257,257,257
BEGIN DESCRIPTION:
527
END DESCRIPTION:
XS GIS Cut Line= 3
      1511061.72      6785266.03      1510652.89      6785156.66
      1509853.36      6785008.21
#Sta/Elev= 30
  4579.6 2231.51  4700.4 2225.73  4721.1 2219.88  4762.5 2196.06  4786.6 2189.98
    4835 2182.97  4876.4  2184.2  4917.8 2181.35  4941.6 2174.02  4969.6  2173.3
  4975.4 2166.69  4975.9 2166.19    4988 2166.69  4999.1 2173.59  5049.4 2175.01
  5112.5  2174.5  5153.2  2185.8  5366.8 2197.41  5397.3 2193.62  5404.4 2196.63
  5409.4 2194.91  5432.2 2202.78  5509.2 2210.85  5590.6 2227.64  5620.7 2229.09
  5683.7 2238.91  5712.6 2236.98  5740.7 2240.51  5789.3 2254.34    5816 2257.81
#Mann= 6 ,-1 , 0
  4579.6     .16       0  4975.4     .07       0    4988     .16       0
  5049.4     .07       0  5432.2     .16       0  5740.7     .07       0
Bank Sta=4975.4,4988
XS Rating Curve= 0 ,0
Exp/Cntr=0.3,0.1

Type RM Length L Ch R = 1 ,15010   ,300,300,300
BEGIN DESCRIPTION:
526
END DESCRIPTION:
XS GIS Cut Line= 3
      1511243.99      6785167.06      1510869.03      6784976.97
      1509838.88      6784987.38
#Sta/Elev= 30
  4516.3 2230.66  4589.8 2229.25  4706.8 2212.33    4768 2221.48  4857.1 2223.29
  4879.3 2215.61  4885.2 2209.08  4901.6 2202.48  4907.6 2195.87  4918.3 2189.05
  4923.9 2189.42  4936.1 2180.08  4960.7 2174.57  4974.4 2166.04  4974.9 2165.54
    4987 2166.04  5010.7 2172.28    5066 2172.46  5110.7 2172.05  5120.7 2175.22
  5170.7 2169.99  5200.7 2180.14  5290.7  2181.7  5550.8 2207.46  5636.9 2209.34
  5670.8 2211.63  5700.8 2223.33  5760.8 2238.02  5884.1 2242.65  5966.9 2260.66
#Mann= 6 ,-1 , 0
  4516.3     .16       0  4974.4     .07       0    4987     .16       0
    5066     .07       0  5636.9     .16       0  5884.1     .07       0
Bank Sta=4974.4,4987
XS Rating Curve= 0 ,0
Exp/Cntr=0.3,0.1

Type RM Length L Ch R = 1 ,14710   ,262,262,262
BEGIN DESCRIPTION:
525
END DESCRIPTION:
XS GIS Cut Line= 3
      1511014.87      6784927.49      1510590.39      6784794.68
      1510095.62      6784760.83
#Sta/Elev= 30
    4570 2219.01  4611.8 2216.85  4632.7 2212.19  4682.7 2207.54  4695.6 2204.25
  4737.5 2198.14  4800.4 2193.15  4810.9 2188.38  4817.8 2181.47    4823 2180.44
  4831.8 2174.87  4842.3 2172.61  4951.5 2169.86  5003.4 2163.67  5003.9 2163.17
    5016 2163.67  5020.2 2168.17  5050.2 2177.93  5090.3 2176.89  5170.5 2181.32
  5190.7 2183.85  5230.7 2192.05  5260.7 2194.96  5297.8 2202.37  5329.1 2210.79
  5334.1 2210.24    5361 2218.45  5401.1 2226.87  5421.1 2235.35  5510.7 2257.57
#Mann= 5 ,-1 , 0
    4570     .16       0  4951.5     .07       0  5003.4     .07       0
    5016     .07       0  5297.8     .16       0
Bank Sta=5003.4,5016
XS Rating Curve= 0 ,0
Exp/Cntr=0.3,0.1

Type RM Length L Ch R = 1 ,14448   ,220,220,220
BEGIN DESCRIPTION:
524
END DESCRIPTION:
XS GIS Cut Line= 3
      1511004.48        6784852.       1510660.7      6784552.49
      1510106.06      6784404.07
#Sta/Elev= 30
    4486 2204.41  4510.1 2207.42  4551.8 2199.37  4658.1 2186.75  4665.8 2188.36
  4743.6 2183.66  4800.6 2178.11  4892.7 2176.03  4921.1 2171.28  4981.4  2167.5
  5003.7 2159.43  5004.2 2158.93  5016.3 2159.43  5051.1 2168.86  5103.1 2170.45
  5131.2 2175.21  5136.4 2172.02  5154.9  2173.8  5196.3 2185.71  5206.1 2194.01
  5211.3  2191.6  5212.9 2193.55    5217 2198.56  5251.3 2202.96  5286.2 2213.45
  5361.1 2226.77  5382.6 2239.84  5446.4 2253.43  5481.3 2271.85  5516.1 2275.44
#Mann= 4 ,-1 , 0
    4486     .16       0  5003.7     .07       0  5016.3     .16       0
  5212.9     .07       0
Bank Sta=5003.7,5016.3
XS Rating Curve= 0 ,0
Exp/Cntr=0.3,0.1

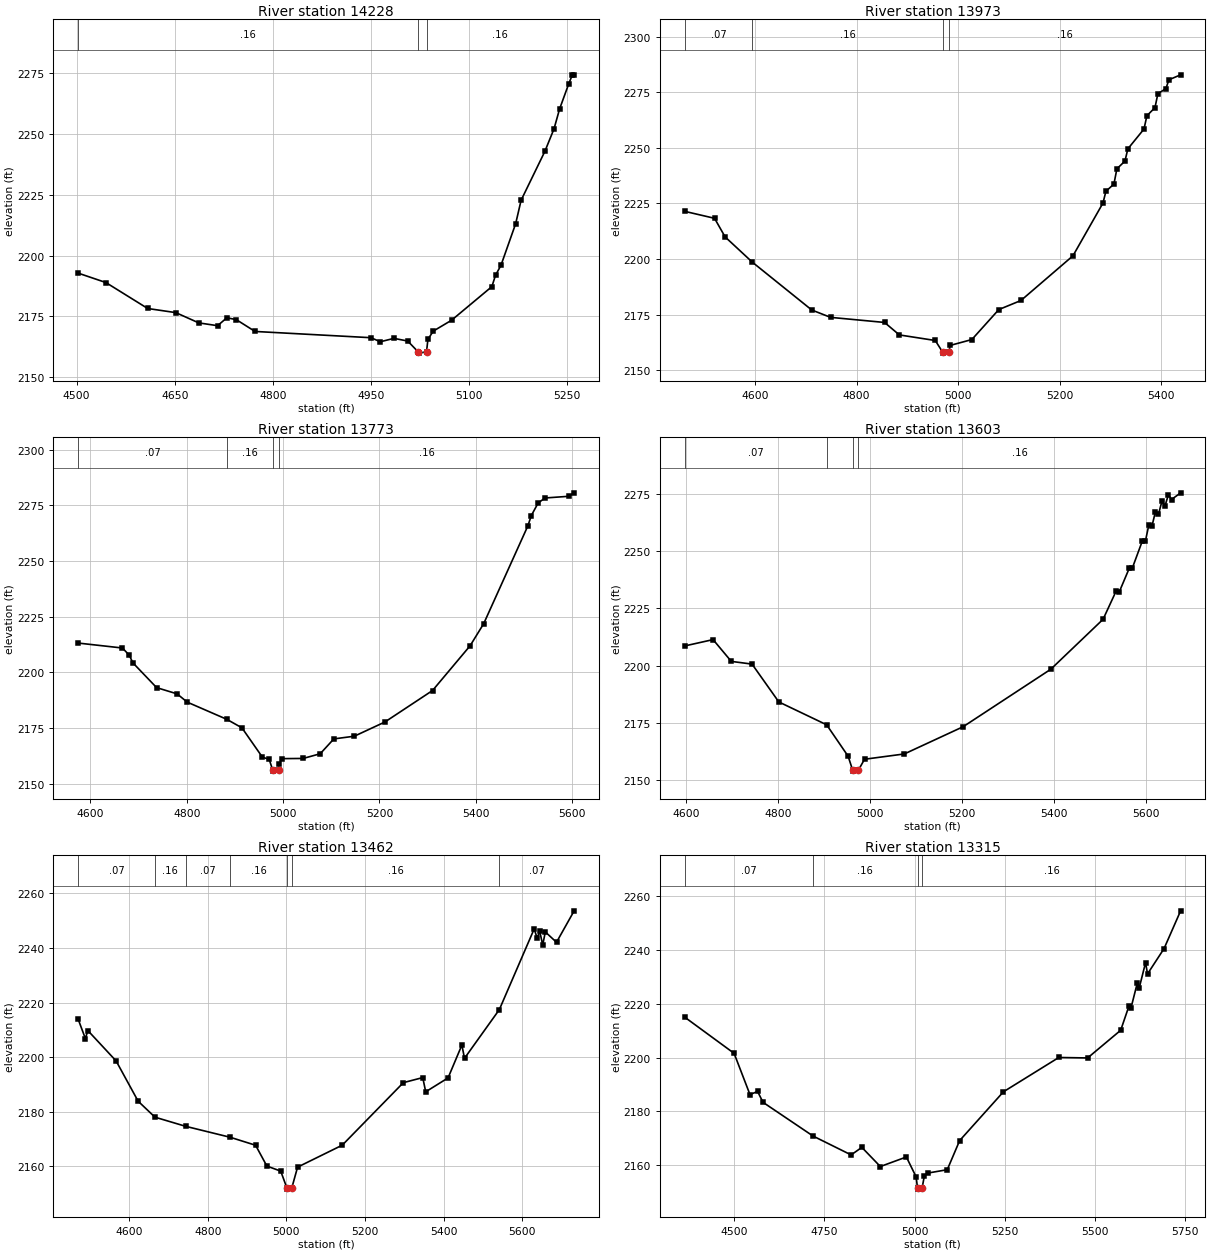
Type RM Length L Ch R = 1 ,14228   ,255,255,255
BEGIN DESCRIPTION:
6
END DESCRIPTION:
XS GIS Cut Line= 3
        1511005.        6784638.      1510621.43      6784321.16
      1510505.01      6784088.01
#Sta/Elev= 30
  4502.5 2192.78  4544.8 2188.92  4608.7 2178.25  4651.7 2176.55  4686.8 2172.33
  4715.5 2171.18  4729.8 2174.44  4744.2 2173.66  4772.8 2168.81    4950 2166.24
  4964.3 2164.57  4985.1 2165.97  5006.2 2164.87  5022.2  2160.4  5022.7  2159.9
  5034.9  2160.4  5037.1  2165.6  5045.3 2168.96  5073.3 2173.44  5134.8 2187.24
  5140.4  2191.9  5148.8 2196.05  5171.2 2213.12  5179.5 2222.74  5215.9 2242.88
  5229.9 2252.17  5238.3 2260.25  5252.2 2270.51  5257.8 2274.31  5260.6 2274.31
#Mann= 3 ,-1 , 0
  4502.5     .16       0  5022.2     .07       0  5034.9     .16       0
Bank Sta=5022.2,5034.9
XS Rating Curve= 0 ,0
Exp/Cntr=0.3,0.1

Type RM Length L Ch R = 1 ,13973   ,200,200,200
BEGIN DESCRIPTION:
523
END DESCRIPTION:
XS GIS Cut Line= 3
       1511158.1      6784716.56      1510835.18      6784292.08
      1510616.44      6783906.67
#Sta/Elev= 30
  4461.6 2221.41  4520.4 2218.28  4541.2 2209.92  4594.8 2198.56  4711.8 2177.06
  4748.8 2173.75  4855.2 2171.46  4884.3 2165.85    4955 2163.35  4969.4 2158.17
  4969.9 2157.67  4982.2 2158.17  4984.1 2161.12    5027 2163.77  5080.1 2177.25
  5123.7 2181.33  5226.1 2201.42  5285.2 2225.13    5291 2230.42  5306.8 2233.68
  5312.6 2240.52  5328.5 2244.01  5334.2  2249.5    5366 2258.42  5371.7 2264.39
  5387.6 2268.03  5393.3 2274.29  5409.2  2276.6    5415 2280.55  5438.1 2282.78
#Mann= 4 ,-1 , 0
  4461.6     .07       0  4594.8     .16       0  4969.4     .07       0
  4982.2     .16       0
Bank Sta=4969.4,4982.2
XS Rating Curve= 0 ,0
Exp/Cntr=0.3,0.1

Type RM Length L Ch R = 1 ,13773   ,170,170,170
BEGIN DESCRIPTION:
522
END DESCRIPTION:
XS GIS Cut Line= 3
      1511309.11      6784583.71      1511025.28      6784266.03
      1510603.43      6783833.77
#Sta/Elev= 30
  4574.5 2213.15  4666.3 2210.93  4680.5 2207.71    4688 2204.28  4737.3 2193.13
  4779.9 2190.32  4800.9 2186.61  4883.1 2178.88  4914.5 2175.06  4957.2 2161.82
    4971 2160.96  4978.4  2156.1  4978.9  2155.6  4991.2  2156.1  4992.3 2158.67
    4997 2161.21  5041.7  2161.3  5077.1 2163.41  5105.4 2170.08  5147.9 2171.29
  5211.4 2177.67  5310.4 2191.83  5388.3 2211.91  5416.6 2221.85  5508.5 2265.88
  5515.5 2270.45  5529.6 2276.06  5543.8 2278.35  5593.3 2279.11  5604.5 2280.67
#Mann= 4 ,-1 , 0
  4574.5     .07       0  4883.1     .16       0  4978.4     .07       0
  4991.2     .16       0
Bank Sta=4978.4,4991.2
XS Rating Curve= 0 ,0
Exp/Cntr=0.3,0.1

Type RM Length L Ch R = 1 ,13603   ,141,141,141
BEGIN DESCRIPTION:
521
END DESCRIPTION:
XS GIS Cut Line= 3
      1511335.18      6784542.08       1511163.3      6784187.91
      1510655.52       6783729.6
#Sta/Elev= 30
  4596.7 2208.61  4658.4 2211.38    4698 2201.86  4743.1 2200.67  4801.3 2184.13
  4905.2 2174.14  4951.8 2160.43  4961.6 2154.39  4962.1 2153.89  4974.4 2154.39
  4987.5 2159.08    5074  2161.4  5201.8  2173.3  5392.3 2198.43  5505.9 2220.26
  5534.3 2232.62  5541.1 2232.24  5562.7 2242.52  5569.5 2242.67  5591.1 2254.44
  5597.9 2254.45  5605.3 2261.49  5612.1 2260.96  5619.5 2267.17  5626.3 2266.19
  5633.7 2271.79  5640.4 2269.79  5647.9 2274.73  5654.6 2272.61  5674.4 2275.54
#Mann= 4 ,-1 , 0
  4596.7     .07       0  4905.2     .16       0  4961.6     .07       0
  4974.4     .16       0
Bank Sta=4961.6,4974.4
XS Rating Curve= 0 ,0
Exp/Cntr=0.3,0.1

Type RM Length L Ch R = 1 ,13462   ,147,147,147
BEGIN DESCRIPTION:
519
END DESCRIPTION:
XS GIS Cut Line= 3
        1511593.      6784495.21      1511262.26      6784088.95
      1510770.11      6783539.51
#Sta/Elev= 30
  4470.6 2213.87  4488.8 2206.83  4495.2 2209.75    4567 2198.62    4623 2183.87
  4665.8 2178.01  4743.9 2174.66  4857.3 2170.64  4921.8 2167.72  4950.5 2160.09
  4985.7 2158.24  5001.2 2152.14  5001.7 2151.64    5014 2152.14  5028.6  2159.7
  5142.2 2167.75  5297.7 2190.67    5347 2192.52  5354.5 2187.31  5411.4 2192.41
  5446.5 2204.44  5453.2 2199.59  5541.8 2217.44  5630.4    2247  5637.9 2243.69
  5644.6 2246.09  5652.1 2241.12  5658.8 2245.91  5687.2 2242.11  5732.1 2253.64
#Mann= 7 ,-1 , 0
  4470.6     .07       0  4665.8     .16       0  4743.9     .07       0
  4857.3     .16       0  5001.2     .07       0    5014     .16       0
  5541.8     .07       0
Bank Sta=5001.2,5014
XS Rating Curve= 0 ,0
Exp/Cntr=0.3,0.1

Type RM Length L Ch R = 1 ,13315   ,223,223,223
BEGIN DESCRIPTION:
520
END DESCRIPTION:
XS GIS Cut Line= 3
      1511731.03      6784542.11      1511382.05      6784016.03
      1511070.12      6783342.78
#Sta/Elev= 30
  4363.6 2215.08  4500.5  2201.6  4544.4 2186.24  4565.5 2187.42  4580.5 2183.37
  4719.1 2170.81  4824.5 2163.79  4854.2  2166.6  4905.4 2159.46  4977.5 2163.02
  5004.5 2155.61  5008.3 2151.55  5008.8 2151.05  5021.2 2151.55  5027.4 2156.06
  5036.8 2157.03  5090.7 2158.28    5125 2169.12  5246.2 2187.28  5399.6 2200.06
  5479.4 2199.89    5571  2210.2  5593.9 2219.24  5599.4 2218.44  5616.8 2227.71
  5622.4 2226.03  5639.8 2235.38  5645.3 2231.18  5691.1 2240.62  5736.9 2254.66
#Mann= 4 ,-1 , 0
  4363.6     .07       0  4719.1     .16       0  5008.3     .07       0
  5021.2     .16       0
Bank Sta=5008.3,5021.2
XS Rating Curve= 0 ,0
Exp/Cntr=0.3,0.1

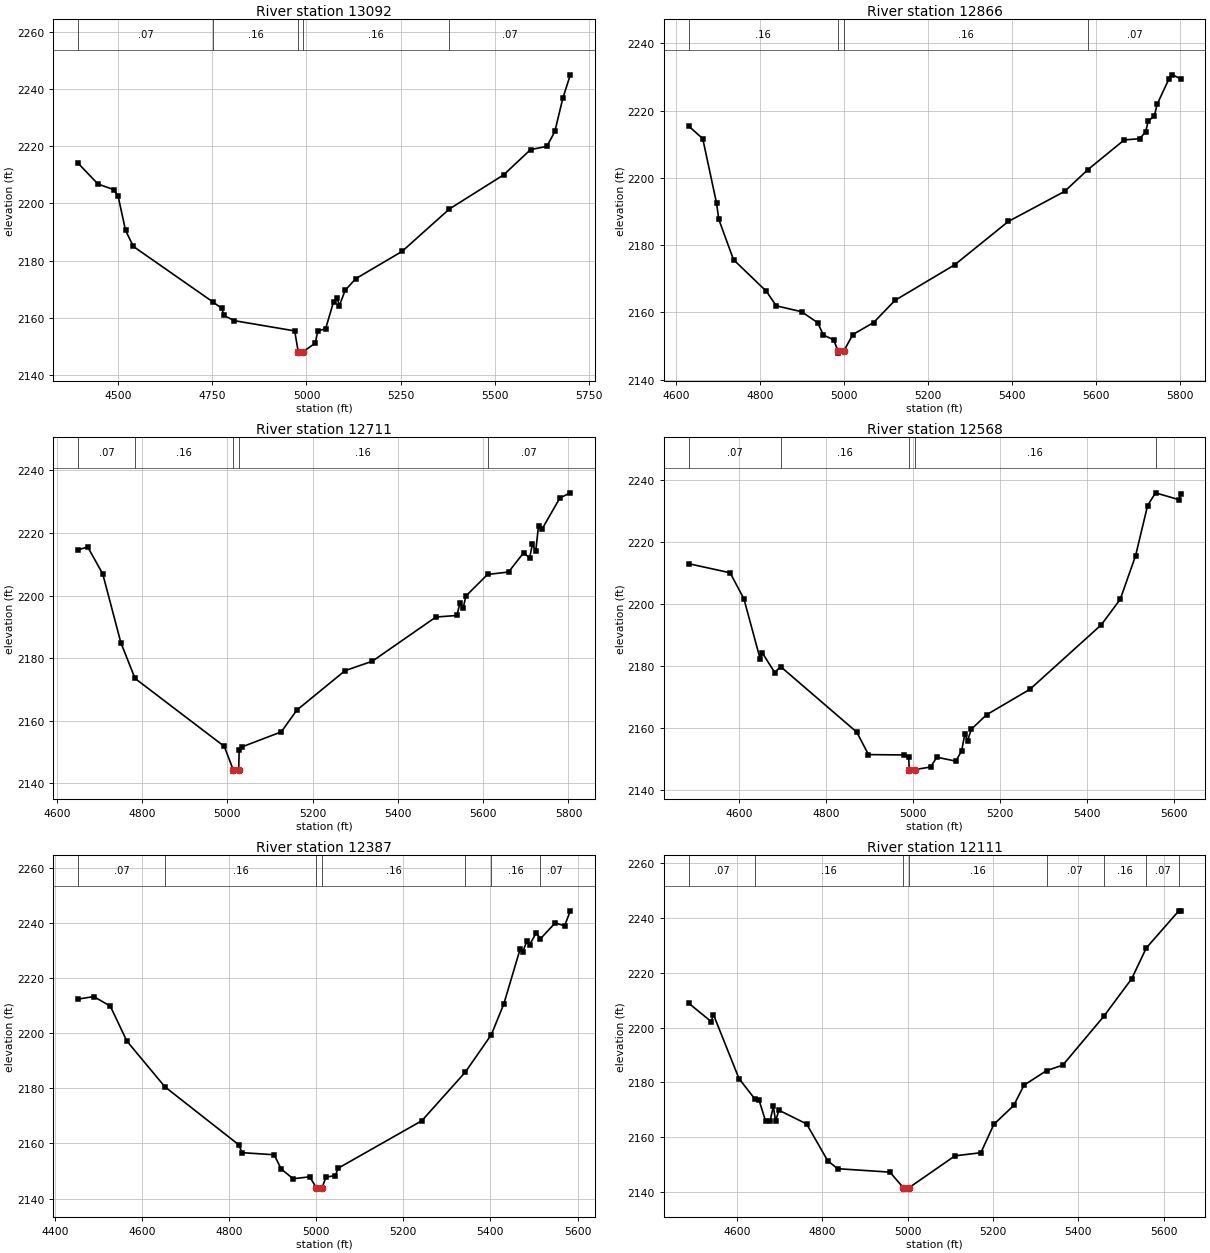
Type RM Length L Ch R = 1 ,13092   ,226,226,226
BEGIN DESCRIPTION:
518
END DESCRIPTION:
XS GIS Cut Line= 3
      1511749.26      6784518.69      1511574.76      6783935.31
      1511197.15      6783349.36
#Sta/Elev= 30
  4393.9 2214.11  4446.8  2206.8  4488.6 2204.86  4500.1 2202.66  4519.9  2190.6
  4540.7 2184.98  4750.9 2165.65  4775.4 2163.31  4780.8 2160.86  4808.5 2159.03
  4968.7 2155.45    4978 2148.18  4978.5 2147.68  4990.9 2148.18  5023.4 2151.17
  5029.7 2155.37  5050.8 2156.23    5072 2165.72  5081.2    2167  5087.1  2164.2
  5102.3 2169.58  5130.5 2173.69  5253.5 2183.25  5379.3  2198.1  5522.8 2209.99
  5594.4 2218.84  5637.7 2219.97  5658.8 2225.18  5679.9 2236.75  5699.9 2244.99
#Mann= 5 ,-1 , 0
  4393.9     .07       0  4750.9     .16       0    4978     .07       0
  4990.9     .16       0  5379.3     .07       0
Bank Sta=4978,4990.9
XS Rating Curve= 0 ,0
Exp/Cntr=0.3,0.1

Type RM Length L Ch R = 1 ,12866   ,155,155,155
BEGIN DESCRIPTION:
517
END DESCRIPTION:
XS GIS Cut Line= 3
      1511889.85      6784315.48       1511783.1      6783963.95
      1511270.11       6783344.2
#Sta/Elev= 30
  4629.7 2215.45  4663.6 2211.67  4696.5 2192.44  4701.7  2187.7  4736.8 2175.69
  4815.2 2166.27  4838.5 2161.96  4898.8 2160.22  4937.1 2156.96    4951 2153.25
  4975.2 2151.87  4985.9  2148.4  4986.4  2147.9  4998.8  2148.4  5020.9 2153.43
  5070.4    2157  5121.3 2163.59  5263.2 2174.15  5390.9 2187.04    5525 2195.99
  5580.5 2202.47    5667  2211.3  5703.5 2211.65  5717.8 2213.68  5724.3    2217
  5738.6 2218.33  5745.1 2221.84  5773.8 2229.55  5781.6 2230.65  5801.6 2229.46
#Mann= 4 ,-1 , 0
  4629.7     .16       0  4985.9     .07       0  4998.8     .16       0
  5580.5     .07       0
Bank Sta=4985.9,4998.8
XS Rating Curve= 0 ,0
Exp/Cntr=0.3,0.1

Type RM Length L Ch R = 1 ,12711   ,143,143,143
BEGIN DESCRIPTION:
516
END DESCRIPTION:
XS GIS Cut Line= 3
      1512163.33      6784070.74      1511889.87      6783851.97
      1511276.35      6783332.04
#Sta/Elev= 30
  4649.9 2214.62  4672.6 2215.52  4707.9  2206.9  4750.2 2184.97  4783.6 2173.48
  4992.8 2151.77  5013.6 2144.35  5014.1 2143.85  5026.6 2144.35  5027.8 2150.75
  5034.4  2151.6  5126.6 2156.41  5162.9 2163.35  5276.1 2175.98  5339.8 2178.98
  5489.2 2193.13  5538.6 2193.62  5545.2 2197.56  5552.9 2195.87  5559.5 2199.86
  5610.2 2206.74  5659.5 2207.52  5694.6 2213.65  5708.9 2212.04  5715.4 2216.43
  5723.2 2214.14  5729.7 2222.28  5737.5 2221.13  5779.9 2231.21  5804.3 2232.84
#Mann= 5 ,-1 , 0
  4649.9     .07       0  4783.6     .16       0  5013.6     .07       0
  5026.6     .16       0  5610.2     .07       0
Bank Sta=5013.6,5026.6
XS Rating Curve= 0 ,0
Exp/Cntr=0.3,0.1

Type RM Length L Ch R = 1 ,12568   ,181,181,181
BEGIN DESCRIPTION:
515
END DESCRIPTION:
XS GIS Cut Line= 3
      1512408.09      6783831.14      1511897.68      6783711.35
      1511414.24      6783342.27
#Sta/Elev= 30
  4483.2  2212.9  4578.8 2209.97  4610.6  2201.6  4647.8 2182.34    4653 2184.18
  4681.5 2177.85    4695 2179.77  4870.3 2158.65  4897.2 2151.42  4979.4 2151.31
  4989.7 2150.61    4991  2146.6  4991.5  2146.1    5004  2146.6    5040 2147.42
  5054.5 2150.57  5098.1 2149.32  5111.5 2152.61  5118.9 2158.06  5125.2  2155.9
  5133.5 2159.54  5168.8 2164.24  5268.6 2172.45  5432.8 2193.21  5476.3 2201.41
  5511.7 2215.46  5539.3 2231.62  5557.5 2235.71  5611.5  2233.5  5615.7 2235.49
#Mann= 5 ,-1 , 0
  4483.2     .07       0    4695     .16       0    4991     .07       0
    5004     .16       0  5557.5     .07       0
Bank Sta=4991,5004
XS Rating Curve= 0 ,0
Exp/Cntr=0.3,0.1

Type RM Length L Ch R = 1 ,12387   ,276,276,276
BEGIN DESCRIPTION:
514
END DESCRIPTION:
XS GIS Cut Line= 3
      1512426.36      6783807.72      1511947.16      6783547.28
      1511439.71      6783255.83
#Sta/Elev= 30
  4452.9 2212.46    4489 2213.37    4527 2209.91    4565 2197.22  4652.5 2180.58
  4821.6 2159.58    4830 2156.66  4903.3 2155.91  4919.5 2150.73    4947 2147.18
    4985  2147.9  5000.2 2143.92  5000.7 2143.42  5013.2 2143.92  5022.5 2147.78
  5044.1 2148.36  5049.9 2150.98  5242.5 2168.27  5342.5 2185.95  5402.2 2199.56
  5430.9 2210.77  5468.3 2230.67    5474 2229.52  5484.1 2233.64  5489.8 2232.16
  5505.6 2236.65  5514.5 2234.31  5548.8 2240.14  5570.4 2239.07  5583.5 2244.53
#Mann= 7 ,-1 , 0
  4452.9     .07       0  4652.5     .16       0  5000.2     .07       0
  5013.2     .16       0  5342.5     .07       0  5402.2     .16       0
  5514.5     .07       0
Bank Sta=5000.2,5013.2
XS Rating Curve= 0 ,0
Exp/Cntr=0.3,0.1

Type RM Length L Ch R = 1 ,12111   ,237,237,237
BEGIN DESCRIPTION:
513
END DESCRIPTION:
XS GIS Cut Line= 3
      1512548.67      6783448.31      1512056.53       6783307.7
      1511421.11      6783219.16
#Sta/Elev= 30
  4486.5 2208.99  4539.7 2202.23  4544.9  2204.8  4604.7 2181.43  4641.9 2173.95
  4651.5 2173.67  4667.1 2165.89  4677.5 2165.88  4685.3 2171.26  4690.5 2165.88
  4698.3 2169.85  4763.3 2164.82  4812.7 2151.36  4836.1 2148.48  4958.3 2147.23
    4990 2141.52  4990.5 2141.02    5003 2141.52  5110.9 2153.19  5171.5 2154.32
  5201.8 2164.68  5248.5 2171.59  5272.5 2178.99  5325.5 2184.33  5363.4 2186.31
  5459.5 2204.16  5524.9 2217.89    5559 2229.11  5634.7 2242.59  5639.9 2242.69
#Mann= 8 ,-1 , 0
  4486.5     .07       0  4641.9     .16       0    4990     .07       0
    5003     .16       0  5325.5     .07       0  5459.5     .16       0
    5559     .07       0  5634.7     .16       0
Bank Sta=4990,5003
XS Rating Curve= 0 ,0
Exp/Cntr=0.3,0.1