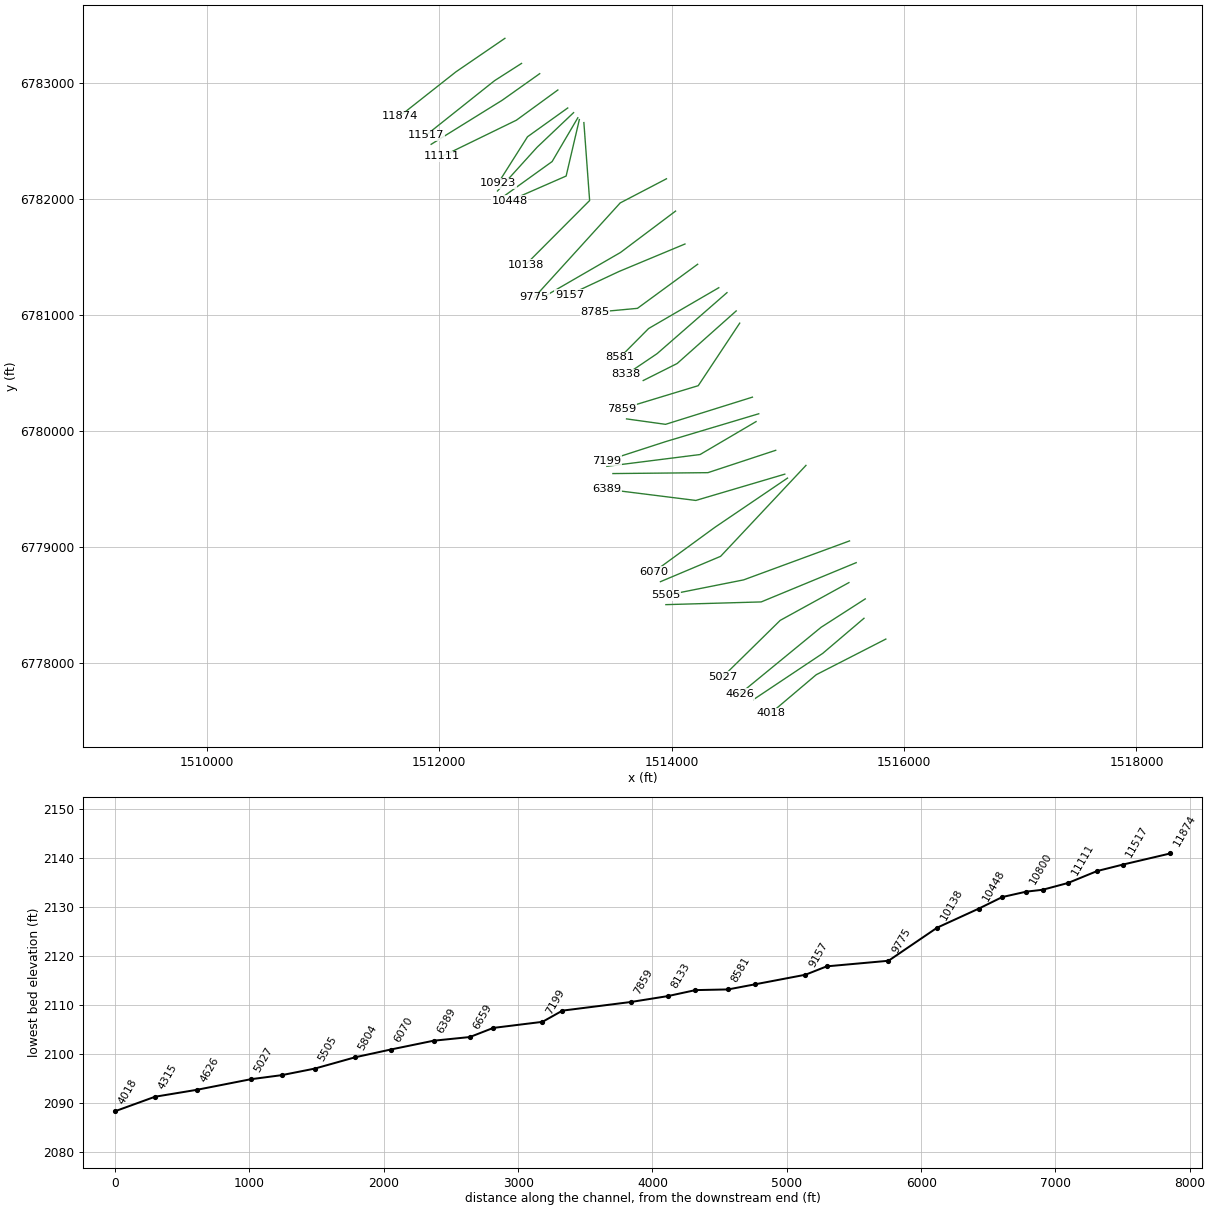
HEC-RAS study Cedar Creek 2.prj: Cedar Creek 2 Base Level Engineering

--- Cedar Creek 2.g01 (geometry) --- (continued)

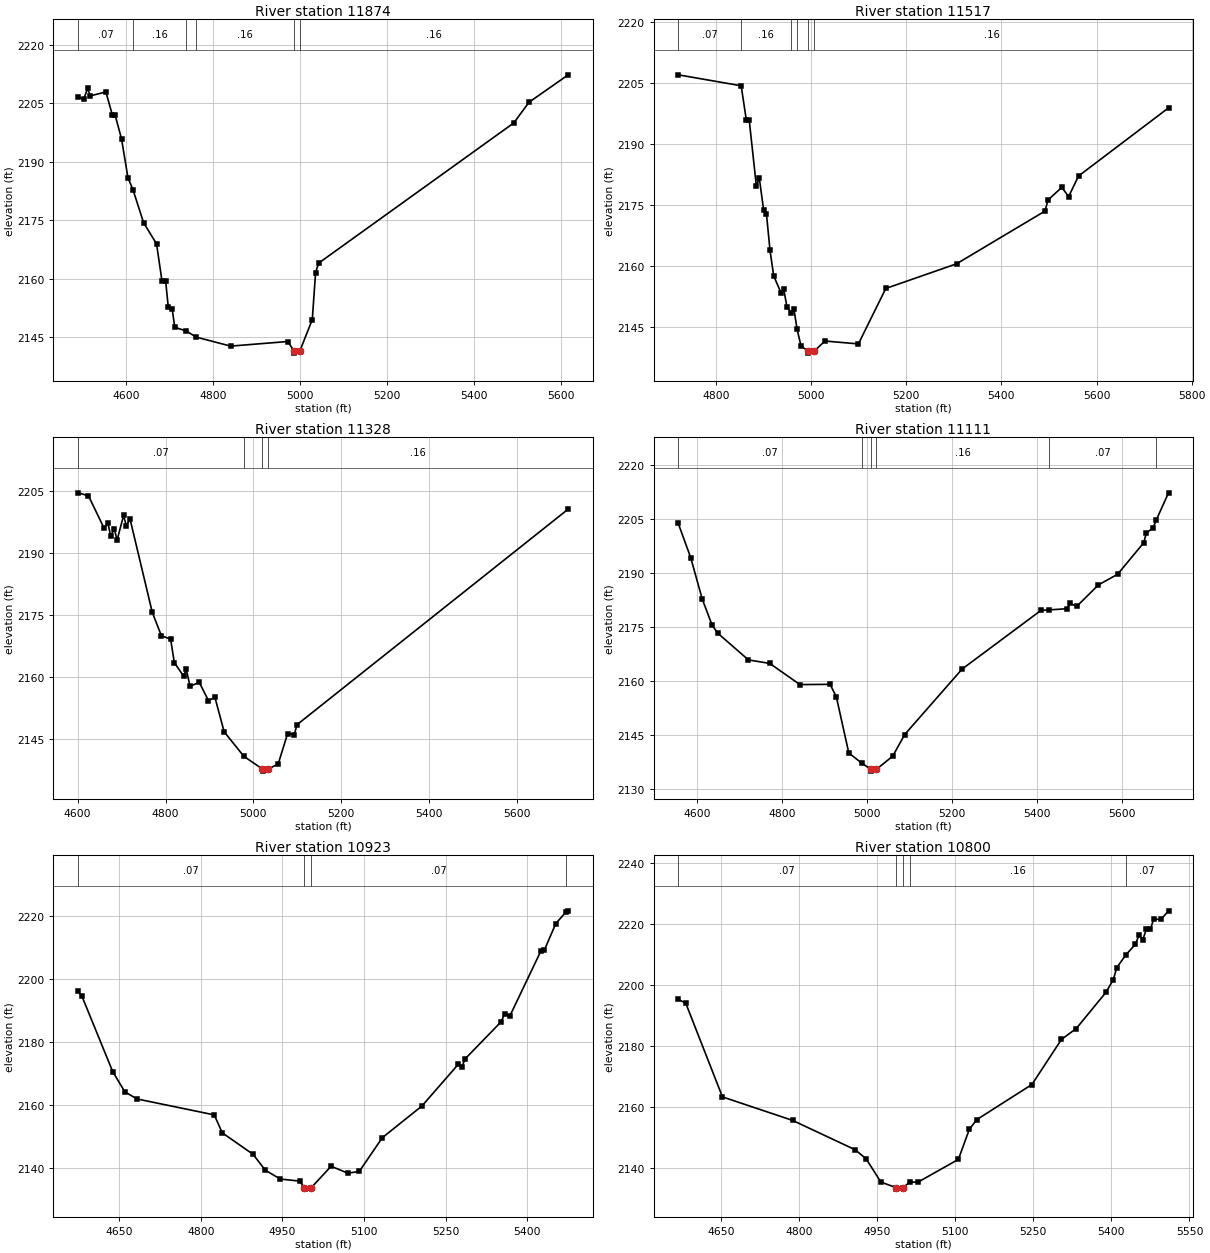
Type RM Length L Ch R = 1 ,11874   ,357,357,357
BEGIN DESCRIPTION:
512
END DESCRIPTION:
XS GIS Cut Line= 3
      1512564.38      6783388.45      1512142.47      6783099.37
      1511659.06      6782717.32
#Sta/Elev= 30
  4489.5 2206.62    4503 2206.14  4511.9 2208.81  4517.9 2206.89  4553.8  2207.9
  4568.7 2201.97  4574.8 2202.06  4589.7 2195.88  4604.6 2185.84  4616.3 2182.75
  4640.5 2174.35  4670.3 2168.91  4682.7 2159.48  4691.3 2159.31  4697.3 2152.65
  4706.2 2152.23  4712.2  2147.5  4738.4 2146.58  4761.5 2144.99  4840.8 2142.68
  4972.2 2143.86  4986.7 2141.38  4987.2 2140.88  4999.7 2141.38  5028.5  2149.5
    5036 2161.49  5042.9 2163.96  5491.7 2199.93    5527 2205.26  5617.1 2212.29
#Mann= 6 ,-1 , 0
  4489.5     .07       0  4616.3     .16       0  4738.4     .07       0
  4761.5     .16       0  4986.7     .07       0  4999.7     .16       0
Bank Sta=4986.7,4999.7
XS Rating Curve= 0 ,0
Exp/Cntr=0.3,0.1

Type RM Length L Ch R = 1 ,11517   ,189,189,189
BEGIN DESCRIPTION:
511
END DESCRIPTION:
XS GIS Cut Line= 3
      1512707.56      6783172.28       1512475.8      6783023.85
      1511884.95      6782552.73
#Sta/Elev= 30
  4720.4 2207.09  4852.8  2204.4  4863.7 2195.93  4869.6 2196.09  4884.8 2179.65
  4890.8 2181.76  4900.1 2173.76    4906 2172.83  4913.4 2163.91  4921.2 2157.59
  4936.4 2153.47  4942.3 2154.27  4949.1 2149.97  4958.5  2148.4  4963.5 2149.54
  4970.5 2144.41  4978.7 2140.31  4993.5 2139.08    4994 2138.58  5006.6 2139.08
  5028.8 2141.56  5099.3 2140.85  5156.9  2154.5  5305.9 2160.58  5491.6 2173.55
    5498 2176.28  5526.9 2179.39  5541.3  2177.1  5562.1 2182.18  5751.3 2198.95
#Mann= 6 ,-1 , 0
  4720.4     .07       0  4852.8     .16       0  4958.5     .07       0
  4970.5     .16       0  4993.5     .07       0  5006.6     .16       0
Bank Sta=4993.5,5006.6
XS Rating Curve= 0 ,0
Exp/Cntr=0.3,0.1

Type RM Length L Ch R = 1 ,11328   ,217,217,217
BEGIN DESCRIPTION:
510
END DESCRIPTION:
XS GIS Cut Line= 3
      1512863.81      6783083.73      1512540.91      6782854.58
      1511929.45      6782474.69
#Sta/Elev= 30
  4600.6 2204.54  4624.5 2203.84  4660.4 2195.92  4668.8 2197.28  4674.9 2194.17
  4683.5 2195.75  4689.7 2193.11  4704.5 2199.07  4710.6  2196.6  4719.2  2198.2
  4769.7 2175.69  4790.6 2169.97  4811.5 2169.21  4819.9 2163.52    4841 2160.25
  4847.1 2161.85  4855.8 2157.79  4876.7 2158.75  4897.6 2154.34  4912.4 2155.09
  4933.3  2146.8  4978.1 2140.87  5020.5 2137.78    5021 2137.28  5033.6 2137.78
  5056.4 2139.03  5077.7 2146.33    5093 2146.04  5098.9 2148.48  5716.4 2200.61
#Mann= 4 ,-1 , 0
  4600.6     .07       0  4978.1     .16       0  5020.5     .07       0
  5033.6     .16       0
Bank Sta=5020.5,5033.6
XS Rating Curve= 0 ,0
Exp/Cntr=0.3,0.1

Type RM Length L Ch R = 1 ,11111   ,188,188,188
BEGIN DESCRIPTION:
509
END DESCRIPTION:
XS GIS Cut Line= 3
      1513020.05       6782943.1       1512663.3       6782682.7
      1512022.64      6782370.18
#Sta/Elev= 30
  4555.5 2203.75    4585 2194.16    4612  2182.7  4635.2 2175.46  4648.4 2173.21
  4720.9 2165.75  4771.1 2164.78  4842.2 2158.89  4913.2 2158.97  4927.9 2155.47
  4957.2 2139.89  4987.3  2137.1  5009.1 2135.34  5009.6 2134.84  5022.2 2135.34
  5060.7 2139.01  5088.8 2145.01    5224 2163.21  5409.8 2179.53  5429.2 2179.66
  5471.8 2179.99  5477.4 2181.46  5494.4 2180.69    5545 2186.61    5590 2189.55
  5651.7 2198.33  5657.6    2201    5674  2202.5  5681.3 2204.67    5710  2212.2
#Mann= 6 ,-1 , 0
  4555.5     .07       0  4987.3     .16       0  5009.1     .07       0
  5022.2     .16       0  5429.2     .07       0  5681.3     .16       0
Bank Sta=5009.1,5022.2
XS Rating Curve= 0 ,0
Exp/Cntr=0.3,0.1

Type RM Length L Ch R = 1 ,10923   ,123,123,123
BEGIN DESCRIPTION:
5
END DESCRIPTION:
XS GIS Cut Line= 3
      1513105.03      6782788.02      1512759.05      6782539.98
      1512505.02      6782138.03
#Sta/Elev= 30
  4574.3 2196.09  4581.7 2194.55  4638.2 2170.69  4660.5  2164.3  4682.4 2162.04
  4824.9 2156.97  4839.6 2151.29  4896.1  2144.5  4918.9 2139.42  4946.5 2136.64
  4982.1    2136  4990.3 2133.96  4990.8 2133.46  5003.4 2133.96  5039.7 2140.72
  5070.3 2138.51  5091.4 2139.06  5133.8 2149.75  5206.7 2159.81  5273.8 2173.08
  5279.7 2172.13  5286.3 2174.77  5352.6 2186.55  5358.5 2189.05  5367.9 2188.19
  5425.5 2208.98  5431.4 2209.08  5452.6 2217.56  5471.7 2221.32  5475.5 2221.61
#Mann= 4 ,-1 , 0
  4574.3     .07       0  4990.3     .07       0  5003.4     .07       0
  5471.7     .07       0
Bank Sta=4990.3,5003.4
XS Rating Curve= 0 ,0
Exp/Cntr=0.3,0.1

Type RM Length L Ch R = 1 ,10800   ,178,178,178
BEGIN DESCRIPTION:
508
END DESCRIPTION:
XS GIS Cut Line= 3
      1513155.49      6782747.81      1512840.39      6782448.33
      1512500.65      6782072.28
#Sta/Elev= 30
  4568.2 2195.34  4582.7  2194.1  4653.2 2163.33  4787.8 2155.63    4908 2145.99
    4929 2143.03  4957.3 2135.41  4986.3 2133.57  4986.8 2133.07  4999.5 2133.57
  5013.5  2135.4  5028.5 2135.35  5106.2 2142.83  5127.1 2152.64  5141.3 2155.85
  5247.4  2167.4  5304.2 2182.21  5332.6 2185.78  5389.4 2197.61  5403.6 2201.77
  5410.3 2205.75  5427.9 2209.96  5446.2 2213.43  5452.9 2216.34  5460.4 2214.98
  5467.1 2218.28  5474.6 2218.28  5481.3 2221.64  5495.5 2221.63  5509.7  2224.4
#Mann= 5 ,-1 , 0
  4568.2     .07       0  4986.3     .07       0  4999.5     .07       0
  5013.5     .16       0  5427.9     .07       0
Bank Sta=4986.3,4999.5
XS Rating Curve= 0 ,0
Exp/Cntr=0.3,0.1

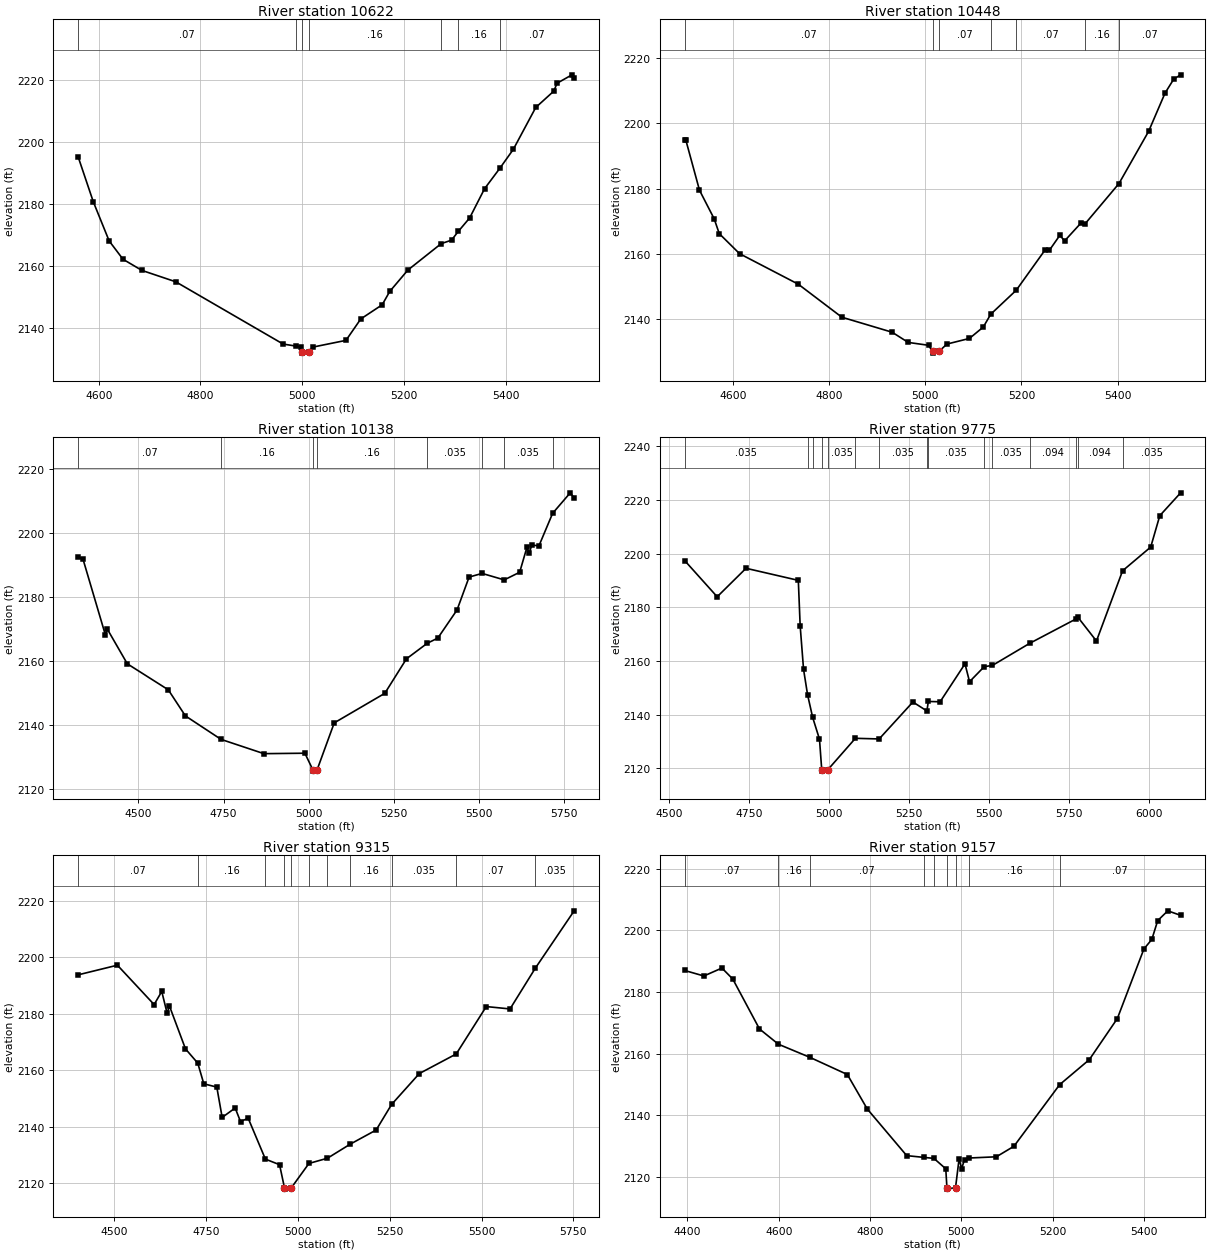
Type RM Length L Ch R = 1 ,10622   ,174,174,174
BEGIN DESCRIPTION:
507
END DESCRIPTION:
XS GIS Cut Line= 3
      1513191.93       6782703.5       1512970.6      6782325.93
      1512534.58      6782011.89
#Sta/Elev= 30
  4559.6 2195.28  4589.2 2180.86  4620.4  2168.2  4647.7 2162.27  4684.9 2158.67
  4751.4    2155  4962.4  2134.9  4987.3 2134.25  4997.3 2133.98  4999.7 2132.47
  5000.2 2131.97  5012.9 2132.47    5021 2133.92    5086 2136.09  5115.1    2143
  5157.2 2147.58    5172 2151.87  5207.6 2158.77  5273.2 2167.32  5293.5 2168.44
  5306.7 2171.25  5329.1  2175.6  5358.5 2185.06  5388.3  2191.6    5415 2197.76
  5459.1 2211.28  5494.7 2216.58  5500.9  2219.1  5530.3 2221.82  5534.6 2220.65
#Mann= 7 ,-1 , 0
  4559.6     .07       0  4987.3     .16       0  4999.7     .07       0
  5012.9     .16       0  5273.2     .07       0  5306.7     .16       0
  5388.3     .07       0
Bank Sta=4999.7,5012.9
XS Rating Curve= 0 ,0
Exp/Cntr=0.3,0.1

Type RM Length L Ch R = 1 ,10448   ,310,310,310
BEGIN DESCRIPTION:
4
END DESCRIPTION:
XS GIS Cut Line= 3
      1513205.01      6782688.02      1513091.37      6782201.21
      1512605.04      6781988.02
#Sta/Elev= 30
  4500.1 2194.76  4502.7 2194.76  4530.9 2179.51  4561.4 2170.76    4572 2166.22
  4614.2 2160.08  4736.3 2150.73  4826.8 2140.62  4931.4 2136.02  4964.7  2132.9
    5007 2132.02  5015.3 2130.12  5015.8 2129.62  5028.5 2130.12  5045.3  2132.4
    5092 2134.12  5120.8 2137.61  5136.4 2141.55  5189.3 2148.88  5248.6 2161.09
  5258.1  2161.1  5279.9  2165.7  5289.9    2164  5324.2 2169.52  5332.2 2169.19
  5402.8 2181.55  5464.4 2197.53  5498.7 2209.29  5516.6 2213.52    5531 2214.86
#Mann= 7 ,-1 , 0
  4500.1     .07       0  5015.3     .07       0  5028.5     .07       0
  5136.4     .16       0  5189.3     .07       0  5332.2     .16       0
  5402.8     .07       0
Bank Sta=5015.3,5028.5
XS Rating Curve= 0 ,0
Exp/Cntr=0.3,0.1

Type RM Length L Ch R = 1 ,10138   ,363,363,363
BEGIN DESCRIPTION:
506
END DESCRIPTION:
XS GIS Cut Line= 3
      1513244.04      6782661.83      1513293.51      6781989.99
       1512741.4      6781435.28
#Sta/Elev= 30
  4323.1 2192.49    4337 2191.94  4403.2 2168.12  4408.2 2170.11  4467.3 2159.22
  4587.6 2151.11  4637.8 2142.97  4742.5 2135.64  4868.4 2131.18  4988.7 2131.32
  5011.7 2126.23  5012.2 2125.73  5024.9 2126.23  5074.9 2140.79  5223.4 2150.01
    5287 2160.78  5348.3 2165.65    5379 2167.24  5435.5 2176.03  5470.9 2186.29
  5509.1 2187.43  5574.1 2185.41  5619.4 2187.79  5640.6 2195.52  5647.7 2193.65
  5654.7 2196.29    5676 2196.03  5716.2 2206.19  5767.9 2212.58  5779.4    2211
#Mann= 8 ,-1 , 0
  4323.1     .07       0  4742.5     .16       0  5011.7     .07       0
  5024.9     .16       0  5348.3    .035       0  5509.1     .07       0
  5574.1    .035       0  5716.2    .063       0
Bank Sta=5011.7,5024.9
XS Rating Curve= 0 ,0
Exp/Cntr=0.3,0.1

Type RM Length L Ch R = 1 ,9775    ,460,460,460
BEGIN DESCRIPTION:
504
END DESCRIPTION:
XS GIS Cut Line= 3
      1513954.94      6782177.48      1513556.53      6781969.16
      1512816.96      6781154.06
#Sta/Elev= 30
    4548 2197.42  4649.6 2183.93  4739.8 2194.55  4903.2 2190.05    4909 2173.07
  4919.6 2156.86  4932.3 2147.31    4948    2139  4969.4 2130.84  4976.4 2119.46
  4976.9 2118.96  4995.3 2119.46  5081.6 2131.19  5155.9 2130.95  5261.4 2144.72
  5305.1 2141.38  5309.6 2144.92  5346.5 2144.81  5424.2 2158.94  5438.4 2152.28
  5484.3 2157.89  5509.9 2158.35  5627.1 2166.63  5769.9 2175.59  5777.6 2176.23
  5835.1 2167.45  5916.8 2193.62  6004.7 2202.46  6033.1 2214.16  6098.2 2222.67
#Mann= 15 ,-1 , 0
    4548    .035       0  4932.3    .063       0    4948    .035       0
  4976.4    .035       0  4995.3    .035       0  5081.6    .063       0
  5155.9    .035       0  5305.1    .094       0  5309.6    .035       0
  5484.3    .094       0  5509.9    .035       0  5627.1    .094       0
  5769.9    .035       0  5777.6    .094       0  5916.8    .035       0
Bank Sta=4976.4,4995.3
XS Rating Curve= 0 ,0
Exp/Cntr=0.3,0.1

Type RM Length L Ch R = 1 ,9315    ,158,158,158
BEGIN DESCRIPTION:
505
END DESCRIPTION:
XS GIS Cut Line= 3
      1514033.09      6781898.84      1513559.14      6781542.08
      1512903.89      6781162.45
#Sta/Elev= 30
  4401.6 2193.75  4508.3 2197.16  4608.3 2183.21  4629.1 2187.86  4643.7 2180.12
    4650 2182.72  4693.7 2167.51  4727.2 2162.45  4743.6 2155.13    4779 2153.97
  4793.6 2143.22    4829 2146.57  4843.6 2141.73  4864.4 2142.96  4911.3 2128.45
  4949.9 2126.48  4963.2 2118.32  4963.7 2117.82  4982.1 2118.32  5029.9 2126.92
  5080.3 2128.77  5142.4 2133.76  5212.9 2138.76    5255 2147.82  5330.5 2158.77
    5431 2165.71  5512.8  2182.5  5577.5 2181.66    5646 2196.03  5752.1 2216.42
#Mann= 11 ,-1 , 0
  4401.6     .07       0  4727.2     .16       0  4911.3     .07       0
  4963.2     .07       0  4982.1     .07       0  5029.9     .16       0
  5080.3     .07       0  5142.4     .16       0    5255    .035       0
    5431     .07       0    5646    .035       0
Bank Sta=4963.2,4982.1
XS Rating Curve= 0 ,0
Exp/Cntr=0.3,0.1

Type RM Length L Ch R = 1 ,9157    ,372,372,372
BEGIN DESCRIPTION:
503
END DESCRIPTION:
XS GIS Cut Line= 3
      1514113.87      6781615.01      1513546.12      6781378.01
      1513119.53      6781177.73
#Sta/Elev= 30
  4393.9 2186.99    4436 2185.21  4475.5 2187.78  4499.3 2184.21  4557.8 2168.03
  4599.3 2163.08  4667.8 2158.86  4750.3 2153.26  4793.8 2142.11  4880.3 2126.97
  4917.3 2126.41  4939.9 2126.08  4965.9  2122.7  4968.4 2116.61  4968.9 2116.11
  4987.3 2116.61  4995.1 2125.95  5000.6 2122.75    5007 2125.69  5017.2  2126.2
  5076.7 2126.59  5115.2    2130  5215.4 2149.98  5280.4 2158.09  5341.8 2171.42
    5400 2193.98  5417.3 2197.05  5430.2 2203.16  5452.3 2206.33  5480.4 2204.87
#Mann= 9 ,-1 , 0
  4393.9     .07       0  4599.3     .16       0  4667.8     .07       0
  4917.3     .16       0  4939.9     .07       0  4968.4     .07       0
  4987.3     .07       0  5017.2     .16       0  5215.4     .07       0
Bank Sta=4968.4,4987.3
XS Rating Curve= 0 ,0
Exp/Cntr=0.3,0.1

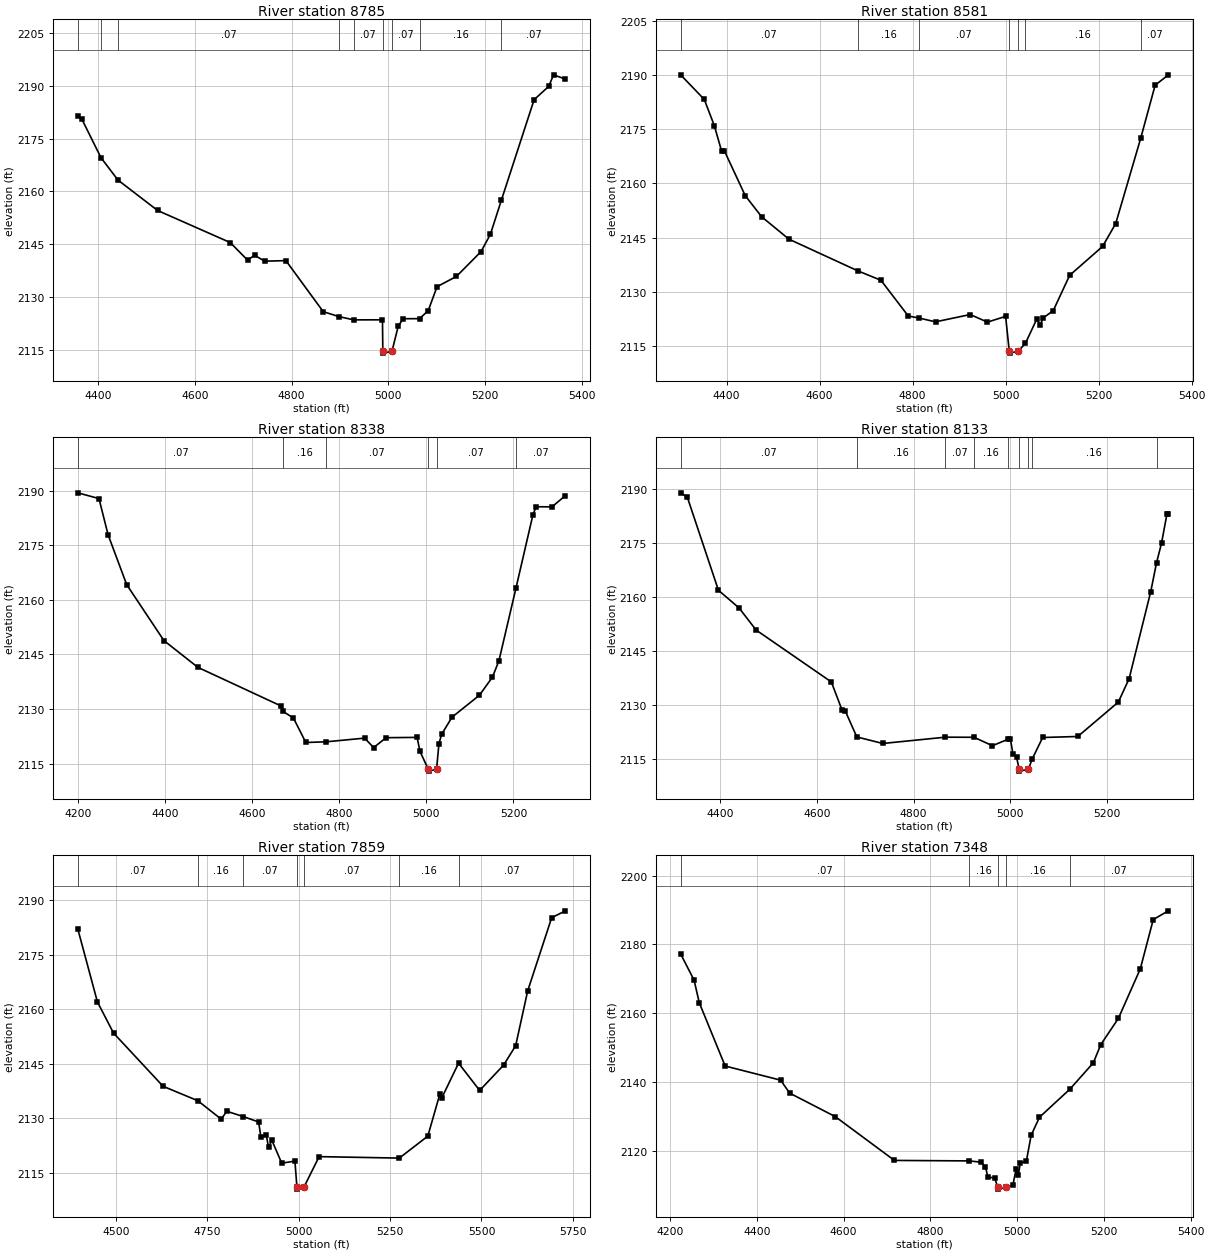
Type RM Length L Ch R = 1 ,8785    ,204,204,204
BEGIN DESCRIPTION:
502
END DESCRIPTION:
XS GIS Cut Line= 3
      1514223.22      6781440.53      1513704.97      6781060.31
      1513340.41      6781026.45
#Sta/Elev= 30
  4357.9 2181.36  4366.3 2180.49  4405.8 2169.57    4441 2163.22    4523  2154.6
  4673.4  2145.5    4709 2140.54  4723.6  2141.9  4744.5 2140.23  4788.4 2140.39
  4865.6 2125.93  4897.6 2124.54  4928.7  2123.6  4988.2 2123.61  4988.9 2114.67
  4989.4 2114.17  5007.8 2114.67  5020.7 2121.77  5030.8 2123.92  5064.9 2123.94
  5082.8 2126.21  5101.1    2133  5141.2 2135.91  5192.2 2142.96  5211.5 2147.88
  5234.1 2157.49  5301.9 2186.01  5332.1 2189.77  5342.1 2193.05  5366.8 2191.83
#Mann= 9 ,-1 , 0
  4357.9     .07       0  4405.8     .16       0    4441     .07       0
  4897.6     .16       0  4928.7     .07       0  4988.9     .07       0
  5007.8     .07       0  5064.9     .16       0  5234.1     .07       0
Bank Sta=4988.9,5007.8
XS Rating Curve= 0 ,0
Exp/Cntr=0.3,0.1

Type RM Length L Ch R = 1 ,8581    ,243,243,243
BEGIN DESCRIPTION:
3
END DESCRIPTION:
XS GIS Cut Line= 3
      1514405.04      6781238.02      1513801.24      6780886.44
        1513555.        6780638.
#Sta/Elev= 30
  4301.3 2190.04  4352.2 2183.23  4373.7    2176  4389.5 2168.91  4395.2 2169.08
  4440.2 2156.65  4475.5  2150.8  4534.2 2144.61  4682.1 2135.86    4732 2133.25
  4790.7 2123.37  4813.8 2122.81  4849.4 2121.76  4923.9 2123.78  4960.9 2121.68
    5000 2123.27  5007.9 2113.61  5008.4 2113.11  5026.9 2113.61  5042.6 2115.82
    5067 2122.52    5074 2120.82  5081.1 2122.88  5102.3 2124.83  5137.7 2134.62
  5208.4 2142.59  5236.7 2148.93  5290.3 2172.44  5321.5 2187.18  5349.8 2190.01
#Mann= 7 ,-1 , 0
  4301.3     .07       0  4682.1     .16       0  4813.8     .07       0
  5007.9     .07       0  5026.9     .07       0  5042.6     .16       0
  5290.3     .07       0
Bank Sta=5007.9,5026.9
XS Rating Curve= 0 ,0
Exp/Cntr=0.3,0.1

Type RM Length L Ch R = 1 ,8338    ,205,205,205
BEGIN DESCRIPTION:
501
END DESCRIPTION:
XS GIS Cut Line= 3
       1514475.8      6781195.72      1513874.24      6780669.68
      1513609.29      6780490.45
#Sta/Elev= 30
  4200.4 2189.37    4249 2187.79  4269.9 2177.85  4312.6 2164.16    4398 2148.81
  4475.9 2141.46  4666.7 2130.86  4671.4 2129.34  4695.1 2127.56  4723.6 2120.83
  4770.6 2121.02  4858.4 2122.03  4879.3 2119.44  4907.7 2122.15  4978.9 2122.23
  4985.6 2118.38  5004.6 2113.47  5005.1 2112.97  5023.6 2113.47    5029 2120.47
  5035.1 2123.06    5059 2127.78  5121.9  2133.8  5151.9 2138.78  5166.8 2143.33
  5205.9 2163.29  5244.8  2183.4  5252.1 2185.55  5288.4 2185.52  5319.4 2188.63
#Mann= 6 ,-1 , 0
  4200.4     .07       0  4671.4     .16       0  4770.6     .07       0
  5004.6     .07       0  5023.6     .07       0  5205.9     .07       0
Bank Sta=5004.6,5023.6
XS Rating Curve= 0 ,0
Exp/Cntr=0.3,0.1

Type RM Length L Ch R = 1 ,8133    ,274,274,274
BEGIN DESCRIPTION:
2
END DESCRIPTION:
XS GIS Cut Line= 3
      1514554.98      6781037.98      1514046.52       6780584.5
      1513754.97      6780437.98
#Sta/Elev= 30
  4318.7 2188.96  4332.5 2187.77  4396.8 2161.93  4439.3 2157.04  4474.6  2150.9
  4630.1 2136.49  4651.8 2128.84  4658.5 2128.55  4682.7 2121.24  4736.3 2119.42
  4865.8 2121.17  4924.8 2121.14  4962.9  2118.8  4995.2  2120.6    5000 2120.71
  5005.3  2116.5  5012.9 2115.55  5018.2 2112.25  5018.7 2111.75  5037.2 2112.25
  5044.9 2115.06  5066.7 2121.08  5139.3 2121.36    5223  2130.9  5245.3 2137.39
    5290 2161.56    5302 2169.57  5312.3 2175.01  5323.5 2183.09  5326.3 2183.09
#Mann= 9 ,-1 , 0
  4318.7     .07       0  4682.7     .16       0  4865.8     .07       0
  4924.8     .16       0  4995.2     .07       0  5018.2     .07       0
  5037.2     .07       0  5044.9     .16       0    5302     .07       0
Bank Sta=5018.2,5037.2
XS Rating Curve= 0 ,0
Exp/Cntr=0.3,0.1

Type RM Length L Ch R = 1 ,7859    ,511,511,511
BEGIN DESCRIPTION:
500
END DESCRIPTION:
XS GIS Cut Line= 3
      1514585.21      6780932.74      1514228.41      6780393.64
      1513569.81       6780193.2
#Sta/Elev= 30
  4395.1 2182.12  4448.8 2162.05  4492.9 2153.49  4628.6 2138.84  4723.5 2134.88
  4787.8 2129.79  4802.8 2131.98  4847.8 2130.52  4890.1 2129.02  4896.1 2124.97
  4911.1 2125.45  4917.1 2122.02  4926.2    2124  4953.3 2117.69  4989.4 2118.26
  4994.9 2111.05  4995.4 2110.55  5013.9 2111.05  5055.6 2119.49  5275.2 2119.09
  5353.2 2125.14    5386 2136.68  5391.3 2135.63  5437.3 2145.21  5495.1  2137.7
  5560.8 2144.69  5593.6 2150.02  5626.5 2165.09  5692.2 2185.24    5730 2187.12
#Mann= 7 ,-1 , 0
  4395.1     .07       0  4723.5     .16       0  4847.8     .07       0
  4994.9     .07       0  5013.9     .07       0  5275.2     .16       0
  5437.3     .07       0
Bank Sta=4994.9,5013.9
XS Rating Curve= 0 ,0
Exp/Cntr=0.3,0.1

Type RM Length L Ch R = 1 ,7348    ,149,149,149
BEGIN DESCRIPTION:
499
END DESCRIPTION:
XS GIS Cut Line= 3
      1514694.59      6780294.69      1513947.16      6780060.31
      1513611.23      6780107.18
#Sta/Elev= 30
  4224.9  2177.2  4255.9 2169.57  4267.8 2163.01  4327.4 2144.59    4455 2140.48
    4476  2136.7  4580.8 2129.88    4717 2117.13  4889.4 2116.99  4916.2 2116.62
  4926.6 2115.25  4932.1 2112.28  4947.6 2112.04    4955 2109.28  4955.5 2108.78
  4974.2 2109.28  4989.5 2109.85    4997 2114.54  5002.2 2112.89  5006.7 2116.43
  5020.5 2116.83  5031.7 2124.43  5050.8 2129.69  5120.8 2137.85  5174.7 2145.51
  5192.1 2150.84  5232.5 2158.46    5283 2172.89  5312.7 2187.19  5347.4 2189.74
#Mann= 5 ,-1 , 0
  4224.9     .07       0  4889.4     .16       0    4955     .07       0
  4974.2     .16       0  5120.8     .07       0
Bank Sta=4955,4974.2
XS Rating Curve= 0 ,0
Exp/Cntr=0.3,0.1

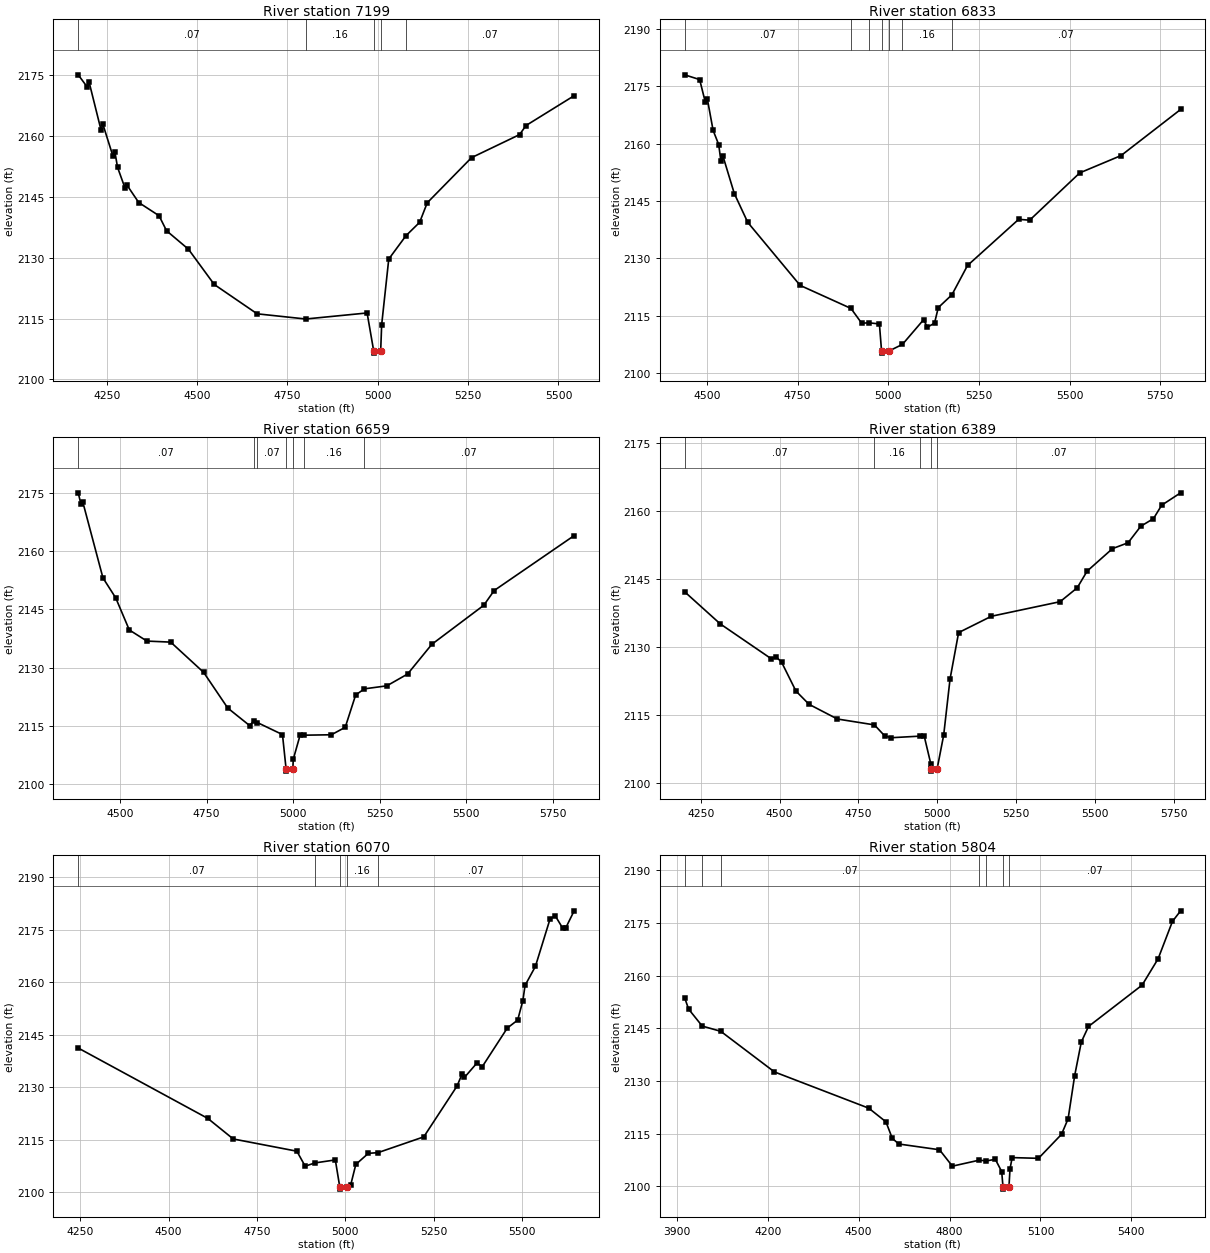
Type RM Length L Ch R = 1 ,7199    ,366,366,366
BEGIN DESCRIPTION:
498
END DESCRIPTION:
XS GIS Cut Line= 3
      1514749.22      6780151.44      1513949.76      6779911.87
      1513438.36      6779745.73
#Sta/Elev= 30
  4171.1 2175.16  4195.8 2172.19  4201.1 2173.41  4234.1 2161.59  4239.4 2162.95
  4267.2  2155.1  4272.4 2156.24  4279.9 2152.35  4300.3 2147.29  4305.5 2148.01
  4338.6 2143.65  4394.7  2140.4  4415.6 2136.68  4476.1 2132.13  4547.5 2123.43
  4666.2 2116.19  4800.6 2114.91  4970.5  2116.4  4988.8 2106.99  4989.3 2106.49
    5008 2106.99  5010.8 2113.53  5030.4  2129.7  5078.1 2135.47  5115.8 2138.76
  5136.9 2143.59  5259.4 2154.72  5392.4 2160.41  5410.2 2162.65  5543.4 2170.01
#Mann= 5 ,-1 , 0
  4171.1     .07       0  4800.6     .16       0  4988.8     .07       0
    5008     .16       0  5078.1     .07       0
Bank Sta=4988.8,5008
XS Rating Curve= 0 ,0
Exp/Cntr=0.3,0.1

Type RM Length L Ch R = 1 ,6833    ,174,174,174
BEGIN DESCRIPTION:
497
END DESCRIPTION:
XS GIS Cut Line= 3
      1514725.85      6780083.77      1514244.03      6779799.89
      1513441.96      6779698.33
#Sta/Elev= 30
  4438.6 2177.97  4479.9 2176.73  4495.5 2170.82  4501.3 2171.55    4517 2163.46
  4532.4 2159.75  4538.4 2155.48  4544.2 2156.71  4575.5 2146.94  4612.6 2139.41
    4757 2122.95  4897.2 2116.93  4926.9 2113.05  4945.8 2113.18  4975.6 2112.88
  4981.6 2105.75  4982.1 2105.25  5000.9 2105.75  5039.2 2107.54  5097.6    2114
  5107.7 2112.02  5127.6 2113.09    5138 2117.15  5175.5 2120.48  5218.6 2128.15
  5359.7 2140.21    5390 2139.99  5528.2 2152.35    5642 2156.87  5806.3 2168.92
#Mann= 7 ,-1 , 0
  4438.6     .07       0  4897.2     .16       0  4945.8     .07       0
  4981.6     .07       0  5000.9     .07       0  5039.2     .16       0
  5175.5     .07       0
Bank Sta=4981.6,5000.9
XS Rating Curve= 0 ,0
Exp/Cntr=0.3,0.1

Type RM Length L Ch R = 1 ,6659    ,270,270,270
BEGIN DESCRIPTION:
494
END DESCRIPTION:
XS GIS Cut Line= 3
      1514895.04      6779836.33      1514311.74      6779643.64
      1513494.08      6779635.83
#Sta/Elev= 30
  4379.2 2174.95  4387.2    2172  4392.4  2172.6  4450.6 2153.08  4487.6 2147.92
  4526.7 2139.69  4577.6 2136.83  4646.3 2136.56  4741.5 2128.77    4811 2119.61
  4874.2  2115.1  4885.6 2116.25  4896.7 2115.87    4969 2112.79  4979.5 2103.89
    4980 2103.39  4998.8 2103.89  5000.2 2106.45  5020.2 2112.74  5030.5 2112.63
  5110.2 2112.74  5150.2 2114.66  5180.3 2122.97  5205.7 2124.55  5270.3 2125.32
  5330.3 2128.36  5400.3    2136  5550.3 2146.04  5580.3 2149.83  5811.2 2163.95
#Mann= 7 ,-1 , 0
  4379.2     .07       0  4885.6     .16       0  4896.7     .07       0
  4979.5     .07       0  4998.8     .07       0  5030.5     .16       0
  5205.7     .07       0
Bank Sta=4979.5,4998.8
XS Rating Curve= 0 ,0
Exp/Cntr=0.3,0.1

Type RM Length L Ch R = 1 ,6389    ,319,319,319
BEGIN DESCRIPTION:
495
END DESCRIPTION:
XS GIS Cut Line= 3
      1514973.23      6779630.63      1514207.57      6779404.06
      1513439.67      6779500.37
#Sta/Elev= 30
  4199.2 2142.24  4312.1 2135.15  4473.2 2127.48  4489.4 2127.88  4506.5 2126.69
  4551.9 2120.33  4593.6 2117.39  4683.3 2114.15  4800.8 2112.85  4833.5 2110.41
  4854.4 2110.02  4945.9 2110.37  4958.6 2110.39  4979.5 2104.26  4980.3 2103.14
  4980.8 2102.64  4999.6 2103.14  5020.4 2110.61  5040.6    2123  5067.7 2133.23
  5171.6 2136.84  5389.6 2140.06  5443.7 2143.12  5475.2 2146.81  5555.6 2151.78
    5605 2153.07  5645.3 2156.72  5685.6 2158.41  5711.6 2161.37  5771.6  2164.1
#Mann= 5 ,-1 , 0
  4199.2     .07       0  4800.8     .16       0  4945.9     .07       0
  4980.3     .07       0  4999.6     .07       0
Bank Sta=4980.3,4999.6
XS Rating Curve= 0 ,0
Exp/Cntr=0.3,0.1

Type RM Length L Ch R = 1 ,6070    ,266,266,266
BEGIN DESCRIPTION:
496
END DESCRIPTION:
XS GIS Cut Line= 3
      1514996.64      6779596.76      1514371.64      6779172.28
      1513849.09      6778790.12
#Sta/Elev= 30
  4244.3 2141.18    4611 2121.05  4682.8 2115.18  4862.8 2111.68  4886.3  2107.4
  4913.8 2108.33  4971.6 2109.19  4984.4 2101.34  4984.9 2100.84  5003.8 2101.34
  5014.9 2101.97  5029.6  2107.9  5065.1 2111.08    5092 2111.26  5221.8 2115.78
    5316 2130.32  5330.2 2133.77  5336.9 2132.77  5372.4 2136.91  5387.1 2135.82
  5458.1 2146.89  5487.4 2149.16  5502.1 2154.73  5508.3 2159.07  5537.6 2164.51
  5579.3 2178.17    5594 2178.92  5615.1  2175.4  5623.3 2175.49  5647.2  2180.4
#Mann= 5 ,-1 , 0
  4244.3     .07       0  4913.8     .16       0  4984.4     .07       0
  5003.8     .16       0    5092     .07       0
Bank Sta=4984.4,5003.8
XS Rating Curve= 0 ,0
Exp/Cntr=0.3,0.1

Type RM Length L Ch R = 1 ,5804    ,299,299,299
BEGIN DESCRIPTION:
491
END DESCRIPTION:
XS GIS Cut Line= 3
      1515155.48      6779706.13      1514421.12      6778922.28
       1513902.9      6778703.54
#Sta/Elev= 30
  3925.9 2153.73  3938.9 2150.51  3983.8 2145.68    4045 2144.19  4222.2 2132.62
  4533.4  2122.3    4590 2118.42    4611 2113.71  4632.5  2112.1  4766.8 2110.46
  4809.3 2105.79    4898  2107.5  4921.5 2107.29    4951 2107.74    4972 2104.26
  4976.5 2099.75    4977 2099.25  4995.9 2099.75  4999.5 2105.03  5006.6 2108.23
  5093.5 2108.02  5169.5 2114.86  5191.2 2119.28  5212.9 2131.59  5234.8 2141.16
  5258.5 2145.57  5435.4 2157.34  5488.2 2164.84  5535.6  2175.5  5562.5  2178.5
#Mann= 7 ,-1 , 0
  3925.9     .07       0  3983.8     .16       0    4045     .07       0
    4898     .16       0  4921.5     .07       0  4976.5     .07       0
  4995.9     .07       0
Bank Sta=4976.5,4995.9
XS Rating Curve= 0 ,0
Exp/Cntr=0.3,0.1

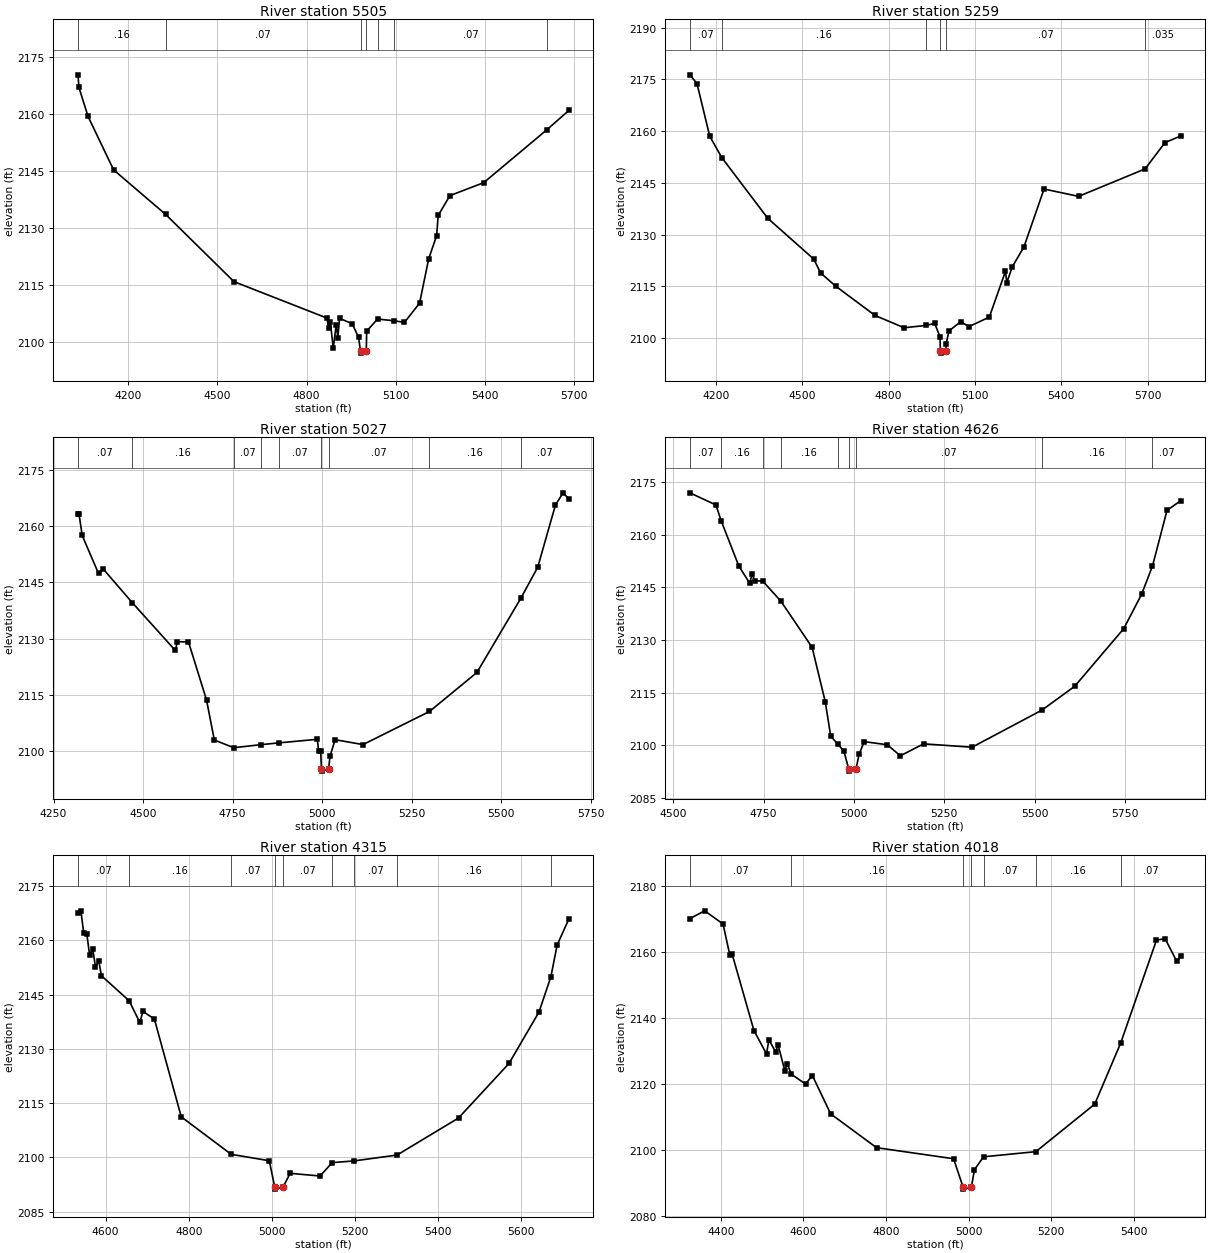
Type RM Length L Ch R = 1 ,5505    ,246,246,246
BEGIN DESCRIPTION:
492
END DESCRIPTION:
XS GIS Cut Line= 3
      1515530.53      6779055.11      1514619.03      6778719.16
      1513952.37      6778586.35
#Sta/Elev= 30
  4031.2 2170.27  4034.5 2166.95    4065 2159.33    4151 2145.24  4326.3 2133.48
  4555.9 2115.78  4868.4 2106.19  4874.8 2103.65  4880.1 2105.08  4889.7 2098.28
  4899.9 2104.47  4905.2    2101    4911 2106.12  4953.6 2104.68    4975 2101.07
  4981.5 2097.45    4982 2096.95  5000.9 2097.45  5002.1 2102.72  5038.6 2105.92
  5095.2 2105.48  5129.1 2105.03  5180.1 2110.12  5210.7 2121.78  5237.5 2127.93
  5242.6 2133.21  5282.1 2138.45  5395.9 2141.86  5609.1 2155.86  5682.4  2160.9
#Mann= 7 ,-1 , 0
  4031.2     .16       0  4326.3     .07       0  4981.5     .07       0
  5000.9     .07       0  5038.6     .16       0  5095.2     .07       0
  5609.1    .035       0
Bank Sta=4981.5,5000.9
XS Rating Curve= 0 ,0
Exp/Cntr=0.3,0.1

Type RM Length L Ch R = 1 ,5259    ,232,232,232
BEGIN DESCRIPTION:
493
END DESCRIPTION:
XS GIS Cut Line= 3
      1515587.81      6778867.61      1514770.07      6778529.06
      1513949.86      6778505.62
#Sta/Elev= 30
  4109.8 2176.32  4134.5 2173.76  4178.7 2158.51  4220.6 2152.32  4380.6 2134.68
  4540.2 2122.88  4564.1 2118.83  4617.3 2114.97    4753 2106.53    4854 2102.97
  4928.3 2103.63  4960.4 2104.22  4978.7 2100.31  4979.9 2096.11  4980.4 2095.61
  4999.5 2096.11  4999.9 2098.35  5009.9 2102.04  5049.9  2104.7    5080 2103.33
    5150 2106.06  5205.9  2119.3  5210.9 2116.08    5230  2120.7    5270 2126.36
  5340.1  2143.2  5460.1 2141.07    5691 2149.03  5760.2 2156.66  5815.4 2158.61
#Mann= 6 ,-1 , 0
  4109.8     .07       0  4220.6     .16       0  4928.3     .07       0
  4979.9     .07       0  4999.5     .07       0    5691    .035       0
Bank Sta=4979.9,4999.5
XS Rating Curve= 0 ,0
Exp/Cntr=0.3,0.1

Type RM Length L Ch R = 1 ,5027    ,401,401,401
BEGIN DESCRIPTION:
490
END DESCRIPTION:
XS GIS Cut Line= 3
       1515525.3      6778695.73      1514934.14       6778370.2
      1514437.94       6777881.8
#Sta/Elev= 30
  4318.2 2163.27    4321 2163.27    4330 2157.47  4375.6 2147.35  4389.4 2148.48
  4470.2 2139.55  4590.1 2126.88  4595.8 2129.19  4626.8 2129.16  4677.2 2113.71
    4699 2103.05  4753.3    2101  4829.2 2101.81  4879.6 2102.29  4986.8 2103.24
  4990.2 2100.03    4996 2100.03  4998.3 2095.27  4998.8 2094.77    5018 2095.27
  5022.3 2098.84  5036.4 2103.13  5114.2 2101.83  5299.9 2110.64  5432.4 2121.02
  5554.9 2140.75  5602.1    2149  5651.6 2165.56  5672.9 2168.81  5689.3 2167.17
#Mann= 9 ,-1 , 0
  4318.2     .07       0  4470.2     .16       0  4753.3     .07       0
  4829.2     .16       0  4879.6     .07       0  4998.3     .07       0
    5018     .07       0  5299.9     .16       0  5554.9     .07       0
Bank Sta=4998.3,5018
XS Rating Curve= 0 ,0
Exp/Cntr=0.3,0.1

Type RM Length L Ch R = 1 ,4626    ,311,311,311
BEGIN DESCRIPTION:
489
END DESCRIPTION:
XS GIS Cut Line= 3
      1515665.88      6778555.08       1515285.7      6778310.31
      1514585.17      6777734.77
#Sta/Elev= 30
    4546    2172  4618.1 2168.53  4632.3 2164.09  4681.5  2151.1  4711.9 2146.15
  4717.8 2148.87  4725.5 2146.94  4747.9 2146.78    4798 2141.07  4884.2 2127.93
  4920.5 2112.44  4935.7 2102.61  4955.1 2100.32    4972  2098.4  4985.8 2093.11
  4986.3 2092.61  5005.5 2093.11  5014.1 2097.37  5028.4 2101.02  5092.3 2100.13
  5128.5 2096.98  5192.7 2100.39  5326.9 2099.43  5520.3 2110.01  5611.1 2116.82
  5746.7 2133.26  5796.2 2143.08  5826.2 2151.09  5866.5    2167  5904.8 2169.79
#Mann= 9 ,-1 , 0
    4546     .07       0  4632.3     .16       0  4747.9     .07       0
    4798     .16       0  4955.1     .07       0  4985.8     .07       0
  5005.5     .07       0  5520.3     .16       0  5826.2     .07       0
Bank Sta=4985.8,5005.5
XS Rating Curve= 0 ,0
Exp/Cntr=0.3,0.1

Type RM Length L Ch R = 1 ,4315    ,297,297,297
BEGIN DESCRIPTION:
1
END DESCRIPTION:
XS GIS Cut Line= 3
      1515654.98      6778387.98       1515299.7      6778085.35
      1514705.03      6777688.02
#Sta/Elev= 30
  4533.3 2167.47  4540.4 2168.18    4547 2162.14  4554.7 2161.68  4561.3    2156
    4569 2157.54  4575.5  2152.6  4583.2  2154.4  4589.8 2150.22  4656.5 2143.31
  4682.1 2137.31  4689.8 2140.34  4717.2 2138.26    4782 2111.19  4902.1 2100.83
  4993.9 2099.05  5007.1  2091.7  5007.6  2091.2  5026.8  2091.7    5044 2095.57
  5116.1 2094.83  5145.3 2098.53  5197.6    2099  5301.5 2100.63  5449.4 2110.87
  5570.9 2125.96  5643.1 2140.18  5671.9 2149.99  5686.7 2158.69  5715.2 2165.97
#Mann= 9 ,-1 , 0
  4533.3     .07       0  4656.5     .16       0  4902.1     .07       0
  5007.1     .07       0  5026.8     .07       0  5145.3     .16       0
  5197.6     .07       0  5301.5     .16       0  5671.9     .07       0
Bank Sta=5007.1,5026.8
XS Rating Curve= 0 ,0
Exp/Cntr=0.3,0.1

Type RM Length L Ch R = 1 ,4018    ,225,225,225
BEGIN DESCRIPTION:
488
END DESCRIPTION:
XS GIS Cut Line= 3
      1515843.02      6778208.76      1515244.03      6777901.45
      1514850.81      6777568.13
#Sta/Elev= 30
  4325.2 2170.03    4361 2172.38  4405.4 2168.41    4422 2158.93  4427.6 2159.24
  4480.3 2136.18  4510.7 2129.12  4516.4 2133.38  4532.9 2129.72  4538.6 2131.88
  4555.1    2124  4560.7 2126.21  4570.4 2123.03  4605.1 2120.01  4621.7 2122.59
  4666.1 2110.98  4777.1 2100.77  4963.6 2097.43  4986.9 2088.74  4987.4 2088.24
  5006.6 2088.74  5014.1  2094.1  5036.1 2098.01  5162.8 2099.57  5305.3 2113.93
  5368.2  2132.4  5454.7 2163.47  5475.5 2164.01  5504.1 2157.07  5513.9 2158.84
#Mann= 7 ,-1 , 0
  4325.2     .07       0  4570.4     .16       0  4986.9     .07       0
  5006.6     .16       0  5036.1     .07       0  5162.8     .16       0
  5368.2     .07       0
Bank Sta=4986.9,5006.6
XS Rating Curve= 0 ,0
Exp/Cntr=0.3,0.1