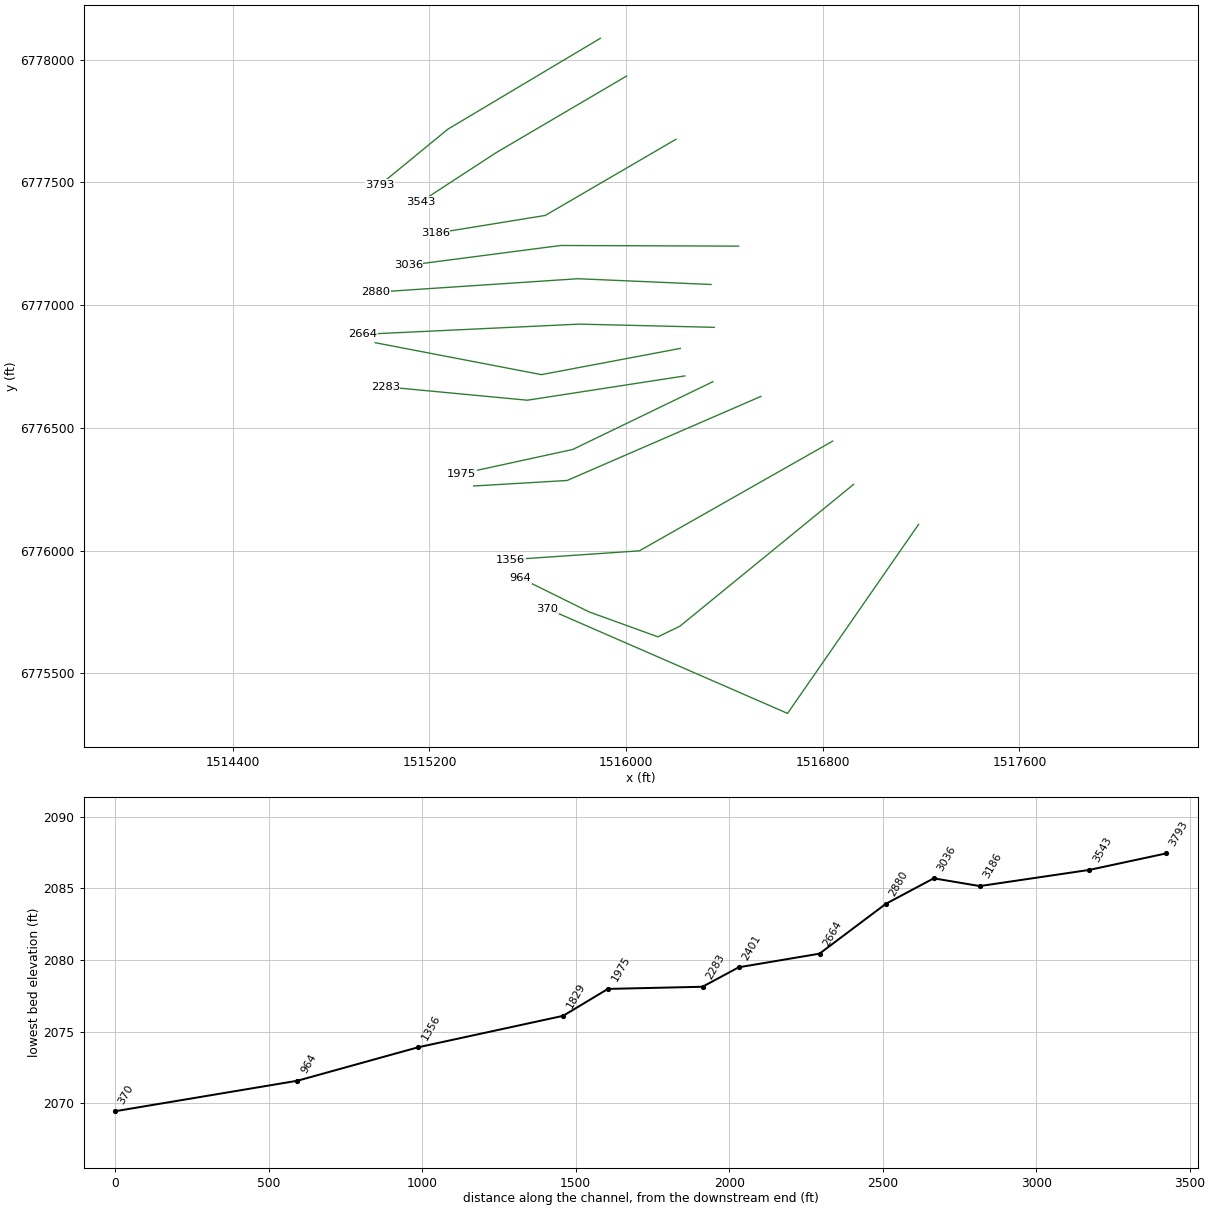
HEC-RAS study Cedar Creek 2.prj: Cedar Creek 2 Base Level Engineering

--- Cedar Creek 2.g01 (geometry) --- (continued)

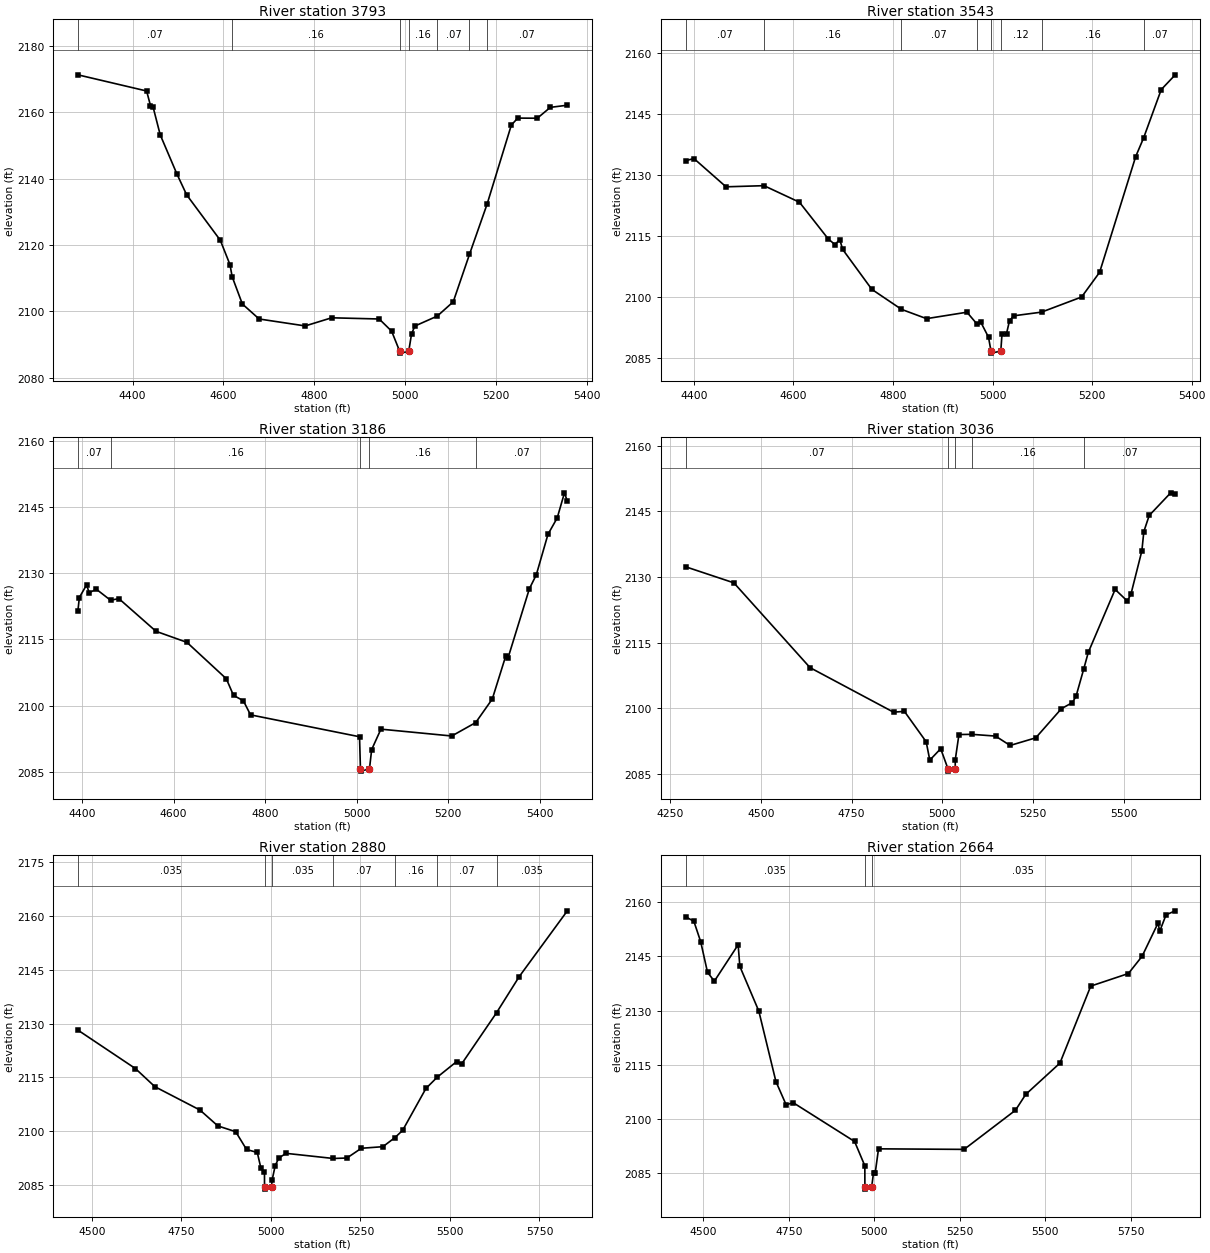
Type RM Length L Ch R = 1 ,3793    ,250,250,250
BEGIN DESCRIPTION:
487
END DESCRIPTION:
XS GIS Cut Line= 3
      1515895.04      6778086.33      1515275.28      6777716.56
      1514999.63      6777490.31
#Sta/Elev= 30
  4279.3 2171.25  4430.7 2166.38  4439.2    2162  4445.1 2161.48  4460.6 2153.21
  4497.6 2141.34    4519 2135.09    4593 2121.44  4614.4 2114.08  4619.1 2110.48
  4641.6 2102.24  4678.6 2097.72  4780.1 2095.63  4838.3 2098.08  4943.1 2097.72
  4970.5 2094.05  4988.4 2087.94  4988.9 2087.44  5008.1 2087.94  5014.3 2093.18
  5021.6 2095.59  5071.1  2098.6  5106.2 2102.89  5141.9 2117.15  5180.9 2132.35
  5234.2 2156.12  5248.3 2158.22  5291.4 2158.18  5320.1 2161.45  5357.6  2162.1
#Mann= 7 ,-1 , 0
  4279.3     .07       0  4619.1     .16       0  4988.4     .07       0
  5008.1     .16       0  5071.1     .07       0  5141.9     .16       0
  5180.9     .07       0
Bank Sta=4988.4,5008.1
XS Rating Curve= 0 ,0
Exp/Cntr=0.3,0.1

Type RM Length L Ch R = 1 ,3543    ,357,357,357
BEGIN DESCRIPTION:
486
END DESCRIPTION:
XS GIS Cut Line= 3
      1516001.88      6777932.72       1515470.6       6777620.2
      1515163.32      6777419.69
#Sta/Elev= 30
  4383.7 2133.53  4400.2 2134.03  4464.6  2127.1  4540.9 2127.38  4612.1 2123.32
  4670.1 2114.29  4683.3 2112.94  4693.1 2114.16  4698.9 2111.74  4757.5 2101.94
  4817.1 2097.03  4867.4 2094.75  4948.6 2096.33  4968.4 2093.48  4976.2 2093.93
  4991.9  2090.2  4996.9 2086.79  4997.4 2086.29  5016.6 2086.79    5019 2090.94
  5028.1  2091.1  5034.1 2094.23  5042.6 2095.45  5098.4 2096.35  5178.9 2100.06
  5215.1 2106.12  5287.6 2134.52  5303.5  2139.1  5338.9 2150.96    5367 2154.58
#Mann= 8 ,-1 , 0
  4383.7     .07       0  4540.9     .16       0  4817.1     .07       0
  4968.4     .12       0  4996.9     .07       0  5016.6     .12       0
  5098.4     .16       0  5303.5     .07       0
Bank Sta=4996.9,5016.6
XS Rating Curve= 0 ,0
Exp/Cntr=0.3,0.1

Type RM Length L Ch R = 1 ,3186    ,150,150,150
BEGIN DESCRIPTION:
485
END DESCRIPTION:
XS GIS Cut Line= 3
      1516202.34      6777674.87      1515671.12      6777364.99
      1515223.22      6777292.08
#Sta/Elev= 30
    4391 2121.46  4394.2  2124.5  4409.9 2127.35  4415.7  2125.6  4431.4 2126.37
  4462.3 2123.88  4480.5 2124.25  4561.6 2116.84  4629.1 2114.34  4715.1 2106.09
  4730.8 2102.33  4752.3 2101.11    4768 2097.91    5006 2092.95    5008 2085.66
  5008.5 2085.16  5027.7 2085.66  5032.5 2090.04  5052.7 2094.67  5207.4 2093.12
  5259.7 2096.16  5295.9  2101.5  5325.4 2111.29  5330.5 2110.88  5376.9 2126.49
    5392 2129.64  5417.5 2138.82  5437.7 2142.54  5453.5 2148.22  5459.8  2146.3
#Mann= 5 ,-1 , 0
    4391     .07       0  4462.3     .16       0    5008     .07       0
  5027.7     .16       0  5259.7     .07       0
Bank Sta=5008,5027.7
XS Rating Curve= 0 ,0
Exp/Cntr=0.3,0.1

Type RM Length L Ch R = 1 ,3036    ,156,156,156
BEGIN DESCRIPTION:
484
END DESCRIPTION:
XS GIS Cut Line= 3
      1516457.62      6777239.99      1515733.62       6777242.6
      1515113.86      6777161.87
#Sta/Elev= 30
  4292.7 2132.34  4425.3 2128.68  4635.3 2109.32  4865.3 2099.16  4895.3 2099.34
  4955.3  2092.4  4965.3 2088.21  4995.3 2090.82  5015.5  2086.2    5016  2085.7
  5035.3  2086.2  5035.5 2088.29  5045.6 2094.05  5081.1  2094.1  5146.4  2093.7
  5186.7 2091.56  5257.3  2093.3  5328.1 2099.96  5358.2 2101.34  5368.3 2102.78
  5389.4 2108.97  5402.1 2112.81  5476.1 2127.18  5509.5 2124.54  5519.5 2126.05
  5549.8    2136  5555.2 2140.38    5570 2144.06  5629.2 2149.23  5641.7  2148.9
#Mann= 5 ,-1 , 0
  4292.7     .07       0  5015.5     .07       0  5035.3     .07       0
  5081.1     .16       0  5389.4     .07       0
Bank Sta=5015.5,5035.3
XS Rating Curve= 0 ,0
Exp/Cntr=0.3,0.1

Type RM Length L Ch R = 1 ,2880    ,216,216,216
BEGIN DESCRIPTION:
482
END DESCRIPTION:
XS GIS Cut Line= 3
      1516345.58      6777083.74      1515803.93      6777107.18
        1514981.      6777052.49
#Sta/Elev= 30
  4460.9 2128.18  4621.6 2117.47  4675.9 2112.43  4801.8 2105.93  4851.8 2101.51
  4901.6  2099.9  4931.9 2094.95  4961.9 2094.12    4972 2089.76    4982 2088.58
  4982.1 2084.42  4982.6 2083.92  5001.9 2084.42  5003.1 2086.35    5012 2090.47
    5022 2092.57  5042.1 2093.88  5174.3 2092.45  5212.2 2092.58  5252.5 2095.29
  5312.7 2095.73  5346.4 2098.27  5367.8 2100.27  5432.9 2111.94  5464.6 2115.09
  5518.3 2119.39  5533.2 2118.85    5630    2133  5693.5 2143.08  5827.8 2161.37
#Mann= 7 ,-1 , 0
  4460.9    .035       0  4982.1    .035       0  5001.9    .035       0
  5174.3     .07       0  5346.4     .16       0  5464.6     .07       0
    5630    .035       0
Bank Sta=4982.1,5001.9
XS Rating Curve= 0 ,0
Exp/Cntr=0.3,0.1

Type RM Length L Ch R = 1 ,2664    ,263,263,263
BEGIN DESCRIPTION:
481
END DESCRIPTION:
XS GIS Cut Line= 3
      1516358.66      6776909.26      1515809.14      6776922.28
      1514928.19      6776880.71
#Sta/Elev= 30
  4448.4    2156  4472.1 2154.77  4492.1 2149.09  4512.1 2140.58  4532.1 2138.16
  4601.6 2148.25  4606.6 2142.25  4662.1 2129.84  4712.1  2110.3  4742.1 2103.82
  4762.1 2104.46  4942.2 2093.66  4972.2 2086.91  4972.3 2080.94  4972.8 2080.44
  4992.1 2080.94  4997.6 2085.01  5002.6 2085.01  5012.2 2091.62  5262.5 2091.47
  5412.7 2102.33  5442.7 2106.72  5542.8 2115.41  5632.9 2136.78    5743 2140.27
  5783.1 2145.06  5829.7 2154.26  5834.7 2152.01  5853.2 2156.56    5880 2157.67
#Mann= 3 ,-1 , 0
  4448.4    .035       0  4972.3    .035       0  4992.1    .035       0
Bank Sta=4972.3,4992.1
XS Rating Curve= 0 ,0
Exp/Cntr=0.3,0.1

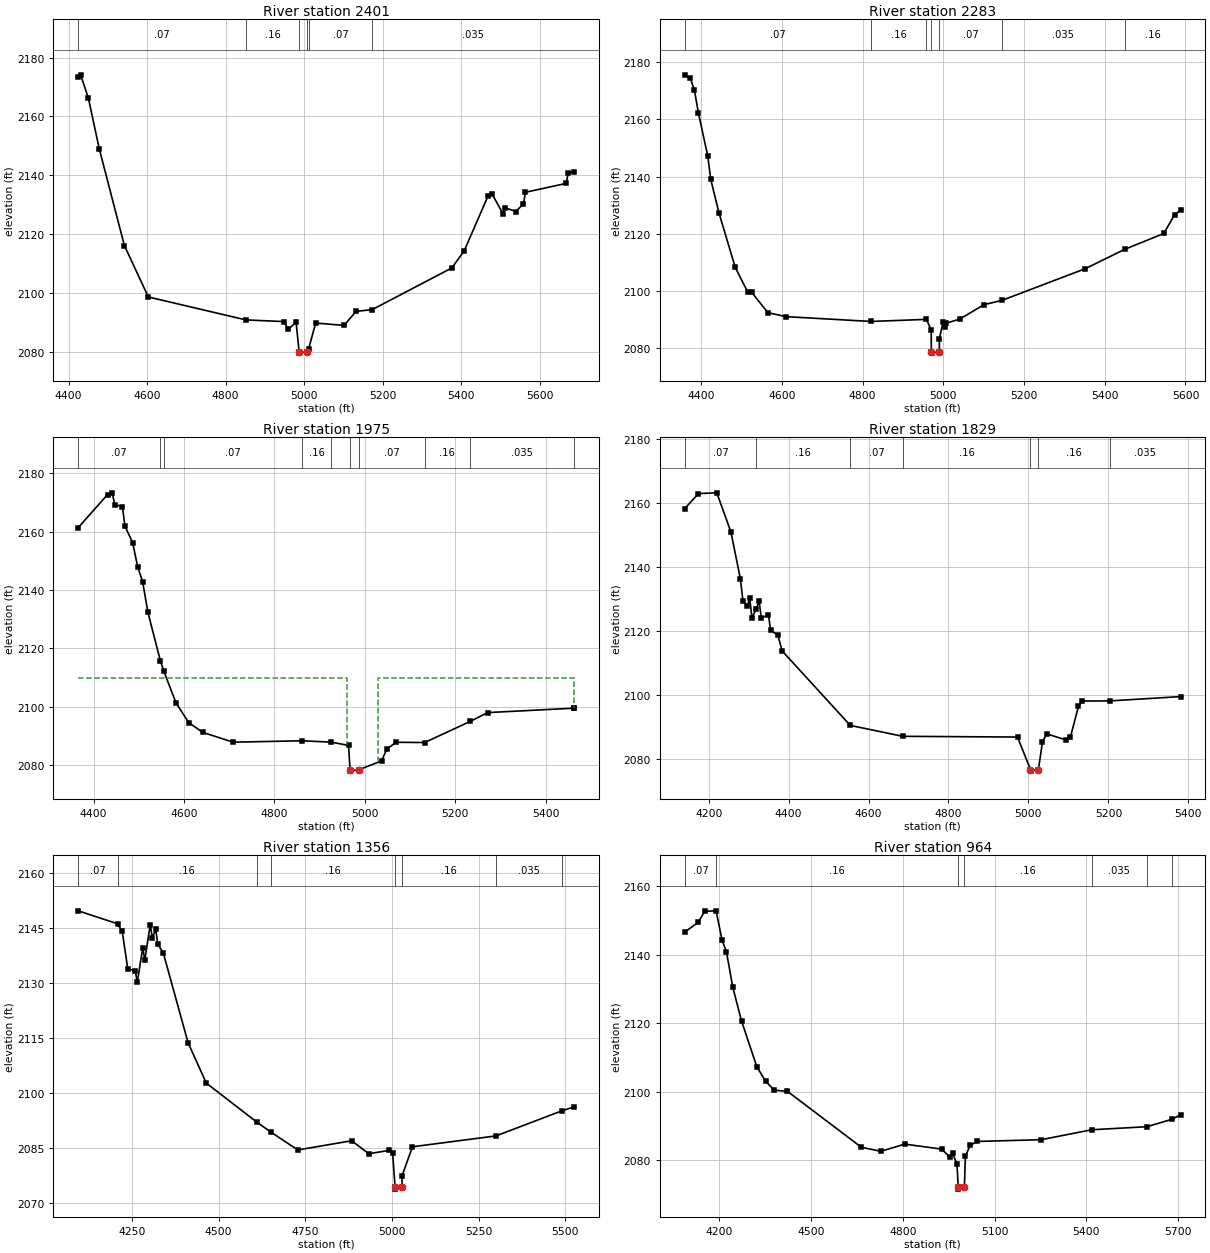
Type RM Length L Ch R = 1 ,2401    ,118,118,118
BEGIN DESCRIPTION:
483
END DESCRIPTION:
XS GIS Cut Line= 3
      1516220.56      6776823.32      1515655.49      6776716.56
      1514979.16      6776846.62
#Sta/Elev= 30
  4424.5 2173.44  4430.7 2174.15  4450.5 2166.16    4478 2149.06  4542.1 2116.09
  4603.2 2098.59  4851.7 2090.79  4949.2 2090.21  4959.4 2087.56  4979.7 2089.99
  4987.4 2079.99  4987.9 2079.49  5007.2 2079.99  5011.4 2080.81  5029.6 2089.73
  5101.9 2088.91  5132.5 2093.69  5173.5 2094.28  5376.9 2108.49  5408.4 2114.37
  5468.5 2132.83  5478.7 2133.72  5507.2 2126.83  5512.3 2128.95  5539.8 2127.65
  5559.1 2130.28  5564.2  2134.2  5668.1 2137.23  5673.2 2140.86  5688.3 2141.19
#Mann= 6 ,-1 , 0
  4424.5     .07       0  4851.7     .16       0  4987.4     .07       0
  5007.2     .16       0  5011.4     .07       0  5173.5    .035       0
Bank Sta=4987.4,5007.2
XS Rating Curve= 0 ,0
Exp/Cntr=0.3,0.1

Type RM Length L Ch R = 1 ,2283    ,308,308,308
BEGIN DESCRIPTION:
480
END DESCRIPTION:
XS GIS Cut Line= 3
      1516238.83      6776711.35       1515598.2      6776612.39
      1515020.11      6776667.07
#Sta/Elev= 30
  4359.1 2175.65  4373.1 2174.53  4383.2 2170.26  4393.3 2162.17  4416.2 2147.23
  4423.7 2139.03  4443.9 2127.34  4484.4 2108.18  4514.8 2099.69  4524.9 2099.48
  4565.3 2092.31  4610.6 2090.91    4821 2089.23  4958.3 2089.96  4970.1 2086.11
  4970.3 2078.63  4970.8 2078.13  4990.2 2078.63  4990.3 2083.23  4999.4 2088.98
  5004.4 2087.22  5006.4 2088.57  5040.7 2090.07  5100.9 2095.11    5146 2096.65
  5352.1 2107.74  5449.2 2114.49  5546.3 2120.05    5573 2126.64    5588 2128.17
#Mann= 7 ,-1 , 0
  4359.1     .07       0    4821     .16       0  4958.3     .07       0
  4970.3     .07       0  4990.2     .07       0    5146    .035       0
  5449.2     .16       0
Bank Sta=4970.3,4990.2
XS Rating Curve= 0 ,0
Exp/Cntr=0.3,0.1

Type RM Length L Ch R = 1 ,1975    ,146,146,146
BEGIN DESCRIPTION:
0
END DESCRIPTION:
XS GIS Cut Line= 3
      1516353.38       6776687.9      1515782.69      6776411.73
      1515330.03      6776313.01
#Sta/Elev= 30
    4366 2161.34  4430.9 2172.66  4441.3 2173.25  4446.8 2169.21  4463.8  2168.5
  4469.4  2161.8  4486.4 2156.24  4497.5 2147.96  4508.6 2142.81  4520.1 2132.38
  4547.7 2115.83  4555.4 2112.19  4582.3 2101.37  4610.5 2094.59  4641.9 2091.23
  4708.6 2087.89  4861.6 2088.37  4925.7  2087.9  4964.1 2086.79  4967.5 2078.48
    4968 2077.98  4987.4 2078.48  5037.2 2081.48  5048.8 2085.52  5069.3 2087.86
  5132.4 2087.77  5233.1 2094.97  5272.2 2098.02    5462 2099.52  5463.3 2099.52
#Mann= 10 ,-1 , 0
    4366     .07       0  4547.7     .16       0  4555.4     .07       0
  4861.6     .16       0  4925.7     .07       0  4967.5     .07       0
  4987.4     .07       0  5132.4     .16       0  5233.1    .035       0
    5462     .07       0
#XS Ineff= 2 , 0
       0    4960    2110    5030       0    2110
Permanent Ineff=
       F       F
Bank Sta=4967.5,4987.4
XS Rating Curve= 0 ,0
Exp/Cntr=0.3,0.1

Type RM Length L Ch R = 1 ,1829    ,473,473,473
BEGIN DESCRIPTION:
479
END DESCRIPTION:
XS GIS Cut Line= 3
      1516548.71      6776628.01        1515760.      6776285.43
      1515379.96        6776263.
#Sta/Elev= 30
  4140.1  2158.3  4174.6 2163.06  4220.5 2163.28  4255.8    2151  4279.3 2136.43
  4285.9  2129.5  4296.8 2127.72  4302.8 2130.31  4308.2 2124.18    4319 2126.82
  4326.2 2129.37  4331.7 2124.16  4349.7 2124.97  4355.1 2120.28  4373.1 2118.68
    4384 2113.75  4554.3 2090.42  4685.5 2087.01  4972.7 2086.77  5005.1  2076.6
  5005.6  2076.1    5025  2076.6  5035.1 2085.25  5045.7 2087.77  5095.2 2085.84
  5105.2  2086.8  5125.2 2096.44  5135.2 2098.06  5202.9 2098.09  5380.7 2099.45
#Mann= 7 ,-1 , 0
  4140.1     .07       0    4319     .16       0  4554.3     .07       0
  4685.5     .16       0  5005.1     .07       0    5025     .16       0
  5202.9    .035       0
Bank Sta=5005.1,5025
XS Rating Curve= 0 ,0
Exp/Cntr=0.3,0.1

Type RM Length L Ch R = 1 ,1356    ,392,392,392
BEGIN DESCRIPTION:
478
END DESCRIPTION:
XS GIS Cut Line= 3
      1516840.42      6776445.74      1516054.03      6775998.85
      1515529.96        6775963.
#Sta/Elev= 30
  4095.5 2149.61  4208.9 2146.09  4222.5 2144.01  4238.4 2133.79    4260 2133.35
  4265.7 2130.15  4281.6  2139.5  4287.4  2136.2  4303.2 2145.82    4309  2142.3
  4319.1 2144.56  4324.9 2140.52  4340.7 2138.18  4412.3  2113.7  4464.7 2102.76
  4610.2 2092.14  4652.2 2089.33  4728.5 2084.56  4883.9 2087.06  4933.3 2083.52
  4992.4 2084.46    5002 2083.65  5009.1  2074.4  5009.6  2073.9    5029  2074.4
  5029.1 2077.52  5059.2 2085.42    5300 2088.38    5489 2095.17  5525.3 2096.29
#Mann= 8 ,-1 , 0
  4095.5     .07       0  4208.9     .16       0  4610.2     .07       0
  4652.2     .16       0  5009.1     .07       0    5029     .16       0
    5300    .035       0    5489     .16       0
Bank Sta=5009.1,5029
XS Rating Curve= 0 ,0
Exp/Cntr=0.3,0.1

Type RM Length L Ch R = 1 ,964     ,594,594,594
BEGIN DESCRIPTION:
786
END DESCRIPTION:
XS GIS Cut Line= 5
      1516925.63      6776269.62      1516218.56      6775691.67
       1516129.4      6775648.62      1515849.63      6775750.08
      1515569.89      6775888.41
#Sta/Elev= 30
  4086.3 2146.55  4130.3 2149.39  4151.7 2152.63  4189.1 2152.76  4208.6 2144.17
  4222.9 2140.79  4243.8  2130.4  4272.5 2120.55    4322 2107.33  4350.7 2103.05
  4379.4 2100.44  4422.5 2100.09  4663.7 2083.81  4727.6  2082.6  4805.9  2084.7
  4926.6 2083.25  4954.5 2080.82  4962.4 2082.06  4976.7 2078.88  4981.1 2072.07
  4981.6 2071.57    5001 2072.07  5004.3 2081.17  5019.8 2084.33  5042.4 2085.48
  5252.1 2085.99  5417.7 2088.89    5598 2089.78  5679.7 2091.94  5708.2 2093.26
#Mann= 7 ,-1 , 0
  4086.3     .07       0  4189.1     .16       0  4981.1     .07       0
    5001     .16       0  5417.7    .035       0    5598     .16       0
  5679.7    .035       0
Bank Sta=4981.1,5001
XS Rating Curve= 0 ,0
Exp/Cntr=0.3,0.1

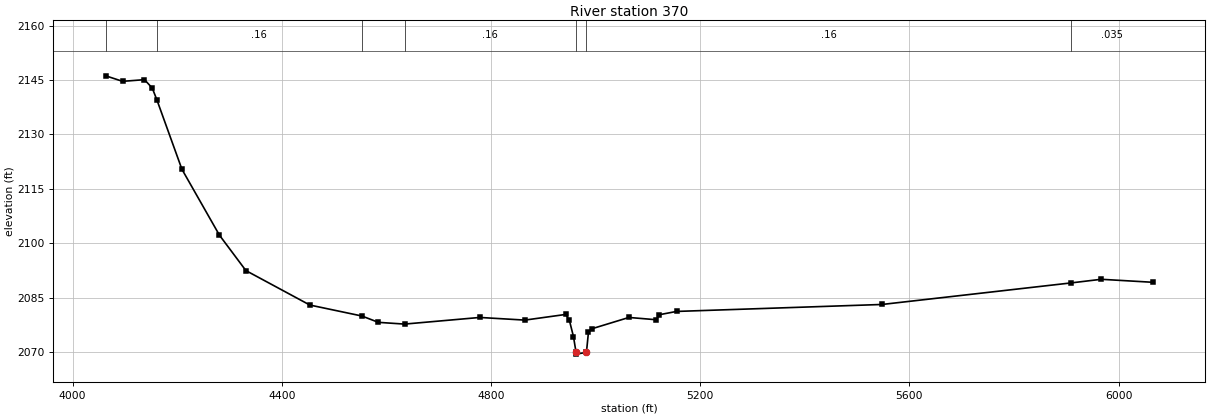
Type RM Length L Ch R = 1 ,370     ,0,0,0
BEGIN DESCRIPTION:
477
END DESCRIPTION:
XS GIS Cut Line= 3
      1517190.08      6776106.72      1516656.87      6775336.83
      1515679.99      6775763.01
#Sta/Elev= 30
  4063.5 2146.16  4095.6 2144.64  4137.5  2145.1  4152.3  2142.8  4161.2 2139.54
  4209.1 2120.39  4280.9 2102.21  4331.4 2092.47  4453.7 2082.97  4553.1 2079.95
  4584.7  2078.2  4634.7 2077.72  4778.6 2079.55  4864.8 2078.82  4942.8 2080.38
  4949.9 2078.74  4957.7 2074.26  4962.6 2069.94  4963.1 2069.44  4982.5 2069.94
  4986.4 2075.59  4993.5 2076.46  5063.7 2079.55    5116 2078.92  5122.1 2080.31
  5154.8 2081.21  5547.6 2083.13  5909.6 2089.08  5966.7 2090.07  6065.8 2089.24
#Mann= 7 ,-1 , 0
  4063.5     .07       0  4161.2     .16       0  4553.1     .07       0
  4634.7     .16       0  4962.6     .07       0  4982.5     .16       0
  5909.6    .035       0
Bank Sta=4962.6,4982.5
XS Rating Curve= 0 ,0
Exp/Cntr=0.3,0.1

Chan Stop Cuts=-1
Use User Specified Reach Order=0
Composite Channel Slope=5