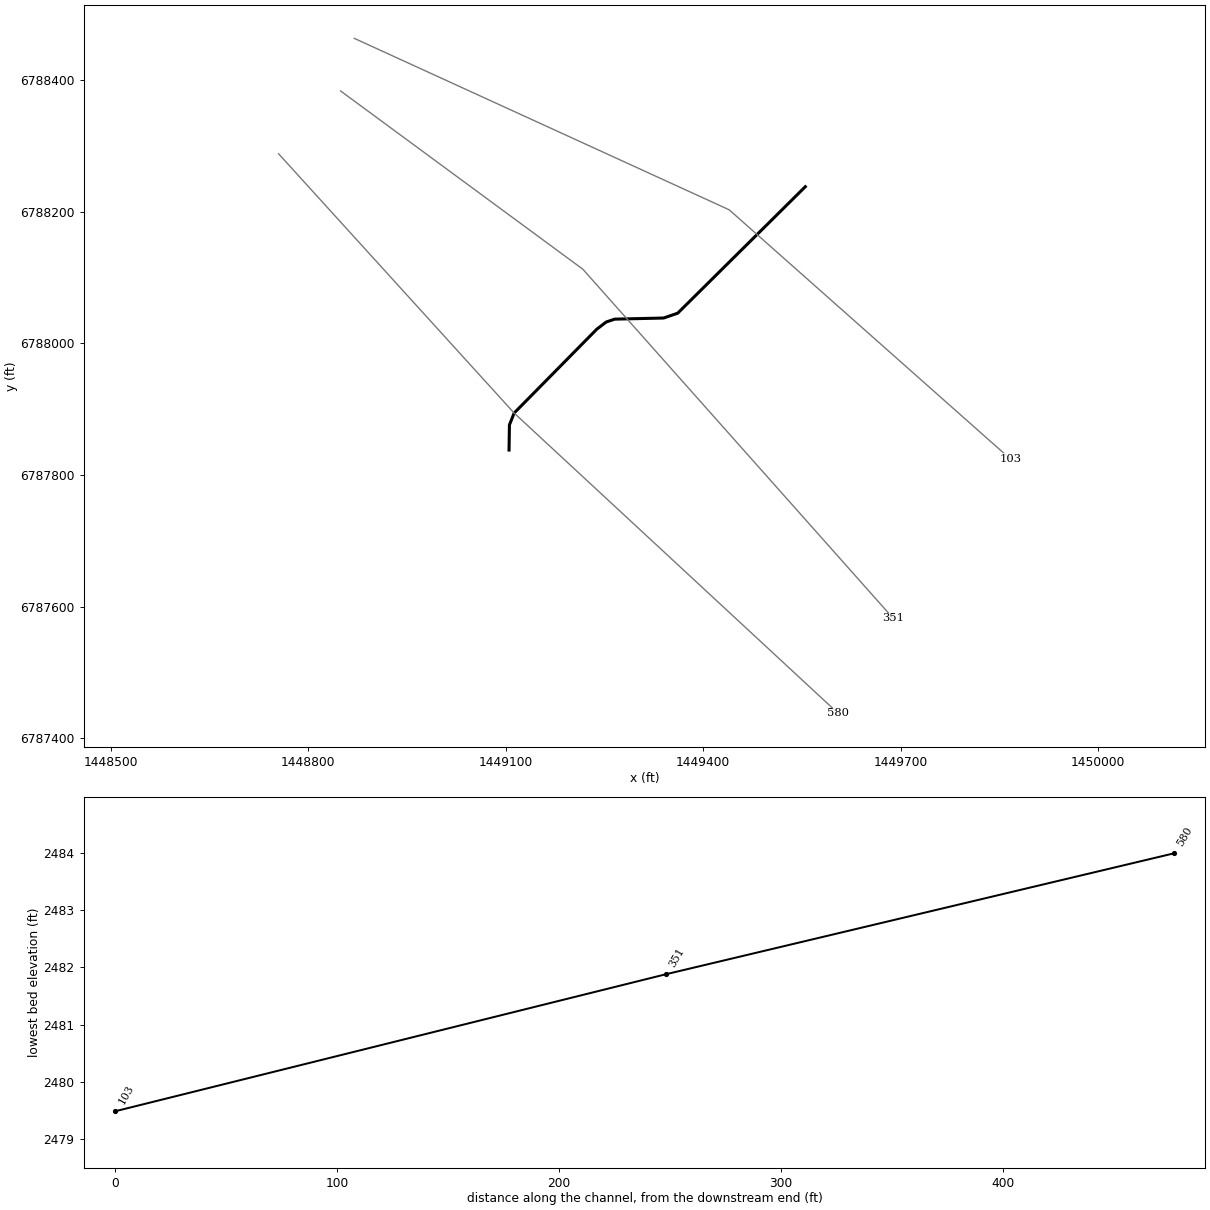
--- Elm 01.prj (project) ---

Proj Title=Elm 01 Base Level Engineering
Current Plan=p01
Default Exp/Contr=0.3,0.1
English Units
Geom File=g01
Flow File=f01
Plan File=p01
BEGIN DESCRIPTION:
Elm 01
END DESCRIPTION:

--- Elm 01.p01 (plan) ---

Plan Title=Multiple Run
Short Identifier=Multiple
Geom File=g01
Flow File=f01
Subcritical Flow
K Sum by GR= 0
Std Step Tol= 0.01
Critical Tol= 0.01
Num of Std Step Trials= 20
Max Error Tol= 0.3
Flow Tol Ratio= 0.001
Split Flow NTrial= 30
Split Flow Tol= 0.02
Split Flow Ratio= 0.02
Log Output Level= 0
Friction Slope Method= 1
Unsteady Friction Slope Method= 2
Unsteady Bridges Friction Slope Method= 1
Parabolic Critical Depth
Global Vel Dist=  1 , 1 , 1
Global Log Level= 0
CheckData=True
Encroach Param= -1, 0, 0, 0
BEGIN DESCRIPTION:
Multiple Run
END DESCRIPTION:

--- Elm 01.f01 (steady flow) ---

Flow Title=Multiple
Number of Profiles=7
Profile Names=10-year,25-year,50-year,1pct_min,100-year,1pct_plu,500-year
River Rch & RM= Elm 01,Reach-1,580
     134     175     205     149     240     330     330
Boundary for River Rch & Prof#=Elm 01,Reach-1,1
Up Type=0
Dn Type=3
Dn Slope=0.005
Boundary for River Rch & Prof#=Elm 01,Reach-1,2
Up Type=0
Dn Type=3
Dn Slope=0.005
Boundary for River Rch & Prof#=Elm 01,Reach-1,3
Up Type=0
Dn Type=3
Dn Slope=0.005
Boundary for River Rch & Prof#=Elm 01,Reach-1,4
Up Type=0
Dn Type=3
Dn Slope=0.005
Boundary for River Rch & Prof#=Elm 01,Reach-1,5
Up Type=0
Dn Type=3
Dn Slope=0.005
Boundary for River Rch & Prof#=Elm 01,Reach-1,6
Up Type=0
Dn Type=3
Dn Slope=0.005
Boundary for River Rch & Prof#=Elm 01,Reach-1,7
Up Type=0
Dn Type=3
Dn Slope=0.005

--- Elm 01.g01 (geometry) ---

Geom Title=Existing Conditions

River Reach=Elm 01,Reach-1
Reach XY= 12
      1449105.00      6787838.00      1449105.59      6787876.16
      1449112.76      6787894.21      1449175.50      6787957.88
      1449238.25      6788021.54      1449252.57      6788032.48
      1449265.48      6788036.83      1449339.78      6788038.53
      1449361.17      6788045.86      1449425.78      6788109.91
      1449490.39      6788173.95      1449555.00      6788238.00

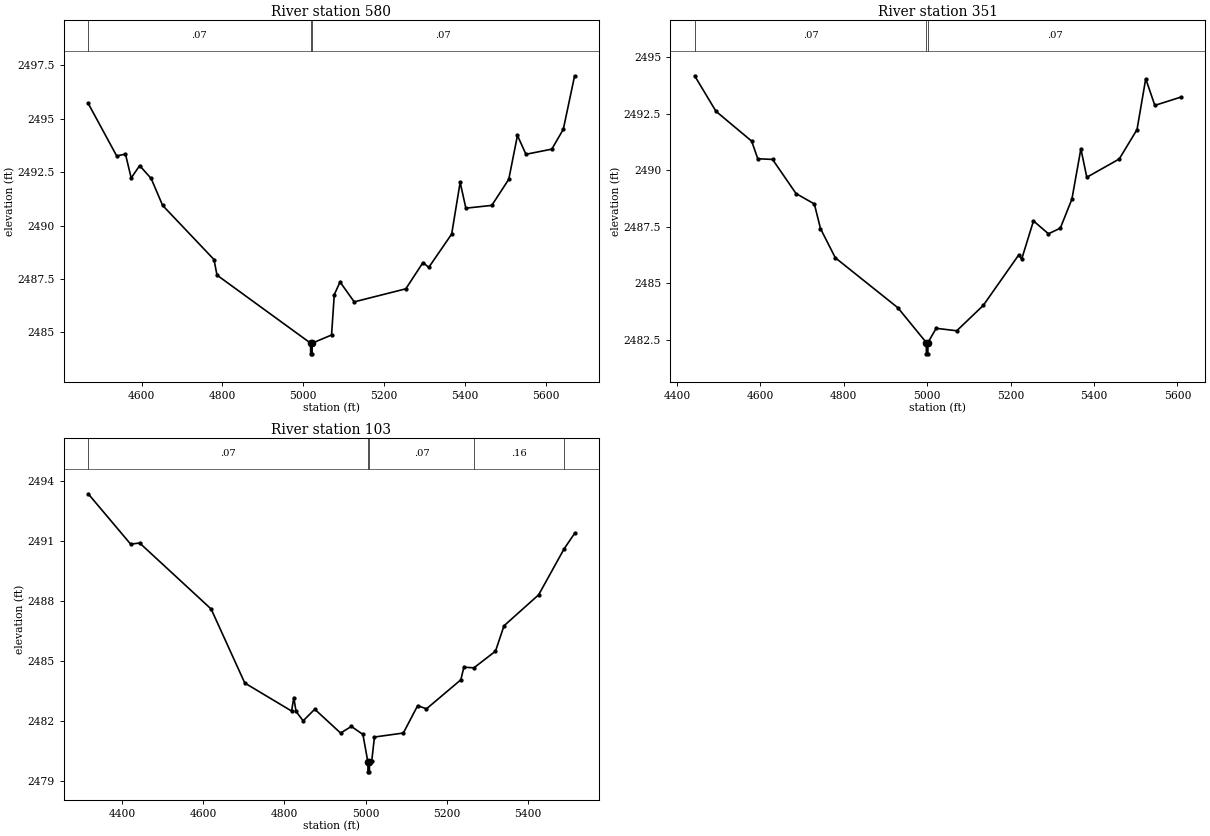
Type RM Length L Ch R = 1,580,229,229,229
BEGIN DESCRIPTION:
elmc181
END DESCRIPTION:
XS GIS Cut Line= 3
      1448755.02      6788287.97      1449112.76      6787894.21
      1449604.97      6787438.03
#Sta/Elev= 30
  4468.0 2495.71  4538.6 2493.25  4560.2 2493.34  4574.4 2492.22  4595.3 2492.80
  4623.7 2492.20  4652.1 2490.94  4779.1 2488.41  4786.6 2487.68  5018.0 2484.50
  5018.3 2484.00  5021.8 2484.00  5022.0 2484.50  5069.9 2484.88  5076.7 2486.77
  5090.9 2487.36  5126.0 2486.43  5253.6 2487.04  5296.1 2488.27  5310.3 2488.04
  5367.0 2489.60  5388.0 2492.02  5402.1 2490.81  5466.2 2490.94  5508.2 2492.16
  5529.7 2494.21  5550.7 2493.33  5614.7 2493.57  5643.1 2494.50  5671.1 2497.00
#Mann=3,-1,0
  4468.0    0.07       0  5018.0    0.07       0  5022.0    0.07       0
Bank Sta=5018,5022
Exp/Cntr=0.3,0.1

Type RM Length L Ch R = 1,351,248,248,248
BEGIN DESCRIPTION:
elmc220
END DESCRIPTION:
XS GIS Cut Line= 3
      1448849.13      6788383.46      1449217.15      6788112.65
      1449688.63      6787582.24
#Sta/Elev= 30
  4442.2 2494.18  4493.3 2492.61  4578.9 2491.29  4593.6 2490.51  4629.0 2490.48
  4685.4 2488.97  4729.3 2488.51  4744.0 2487.42  4779.5 2486.13  4929.5 2483.92
  4997.7 2482.38  4998.0 2481.88  5001.5 2481.88  5001.7 2482.38  5021.5 2483.01
  5070.8 2482.90  5134.3 2484.02  5219.6 2486.26  5226.5 2486.07  5254.8 2487.76
  5290.7 2487.19  5319.1 2487.44  5346.9 2488.72  5368.5 2490.95  5382.7 2489.69
  5460.5 2490.50  5503.1 2491.80  5524.0 2494.05  5545.8 2492.87  5608.8 2493.24
#Mann=3,-1,0
  4442.2    0.07       0  4997.7    0.07       0  5001.7    0.07       0
Bank Sta=4997.7,5001.7
Exp/Cntr=0.3,0.1

Type RM Length L Ch R = 1,103,0,0,0
BEGIN DESCRIPTION:
elmc219
END DESCRIPTION:
XS GIS Cut Line= 3
      1448869.91      6788463.36      1449439.38      6788202.93
      1449866.43      6787824.48
#Sta/Elev= 30
  4317.2 2493.38  4421.8 2490.86  4443.8 2490.92  4619.7 2487.62  4702.5 2483.92
  4817.6 2482.52  4823.1 2483.19  4828.6 2482.50  4846.1 2482.03  4874.6 2482.61
  4938.2 2481.42  4964.7 2481.75  4993.1 2481.35  5005.3 2479.98  5005.6 2479.48
  5009.1 2479.48  5009.3 2479.98  5014.9 2480.03  5021.5 2481.22  5092.6 2481.42
  5127.8 2482.79  5149.5 2482.63  5234.0 2484.08  5241.5 2484.71  5266.2 2484.68
  5319.3 2485.51  5340.2 2486.78  5425.5 2488.33  5488.2 2490.63  5514.0 2491.40
#Mann=5,-1,0
  4317.2    0.07       0  5005.3    0.07       0  5009.3    0.07       0
  5266.2    0.16       0  5488.2    0.07       0
Bank Sta=5005.3,5009.3
Exp/Cntr=0.3,0.1

Chan Stop Cuts=-1