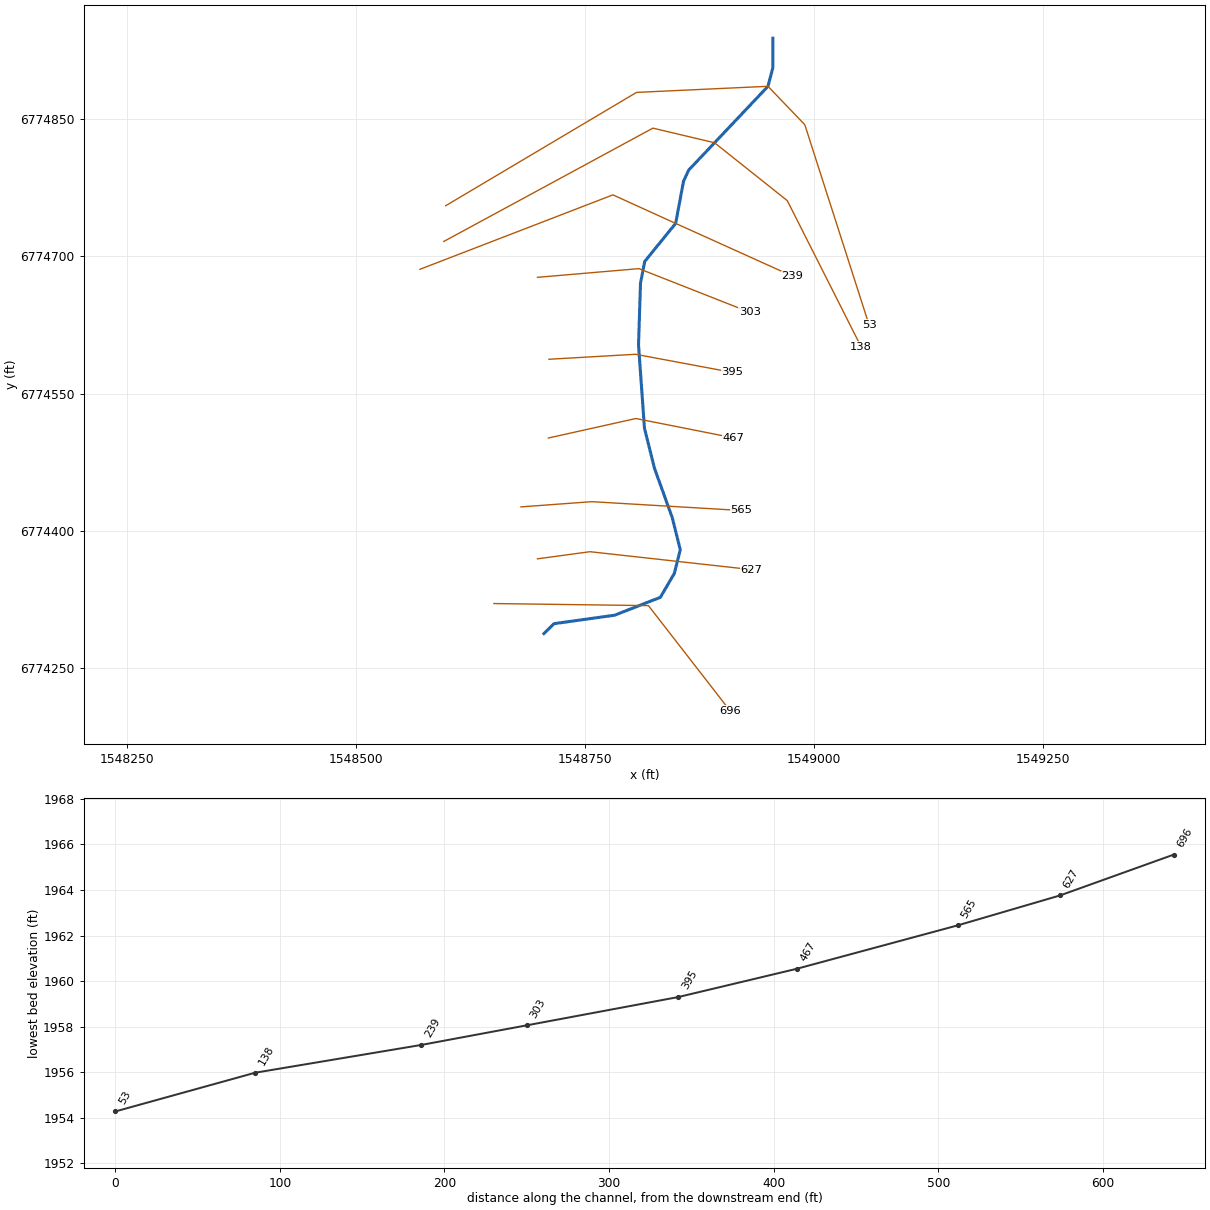
--- Elm 01 00.prj (project) ---

Proj Title=Elm 01 00 Base Level Engineering
Current Plan=p01
Default Exp/Contr=0.3,0.1
English Units
Geom File=g01
Flow File=f01
Plan File=p01
BEGIN DESCRIPTION:
Elm 01 00
END DESCRIPTION:

--- Elm 01 00.p01 (plan) ---

Plan Title=Multiple Run
Short Identifier=Multiple
Geom File=g01
Flow File=f01
Subcritical Flow
K Sum by GR= 0
Std Step Tol= 0.01
Critical Tol= 0.01
Num of Std Step Trials= 20
Max Error Tol= 0.3
Flow Tol Ratio= 0.001
Split Flow NTrial= 30
Split Flow Tol= 0.02
Split Flow Ratio= 0.02
Log Output Level= 0
Friction Slope Method= 1
Unsteady Friction Slope Method= 2
Unsteady Bridges Friction Slope Method= 1
Parabolic Critical Depth
Global Vel Dist=  1 , 1 , 1
Global Log Level= 0
CheckData=True
Encroach Param= -1, 0, 0, 0
BEGIN DESCRIPTION:
Multiple Run
END DESCRIPTION:

--- Elm 01 00.f01 (steady flow) ---

Flow Title=Multiple
Number of Profiles=7
Profile Names=10-year,25-year,50-year,1pct_min,100-year,1pct_plu,500-year
River Rch & RM= Elm 01 00,Reach-1,696
      11      12      13       8      13      18      15
Boundary for River Rch & Prof#=Elm 01 00,Reach-1,1
Up Type=0
Dn Type=3
Dn Slope=0.005
Boundary for River Rch & Prof#=Elm 01 00,Reach-1,2
Up Type=0
Dn Type=3
Dn Slope=0.005
Boundary for River Rch & Prof#=Elm 01 00,Reach-1,3
Up Type=0
Dn Type=3
Dn Slope=0.005
Boundary for River Rch & Prof#=Elm 01 00,Reach-1,4
Up Type=0
Dn Type=3
Dn Slope=0.005
Boundary for River Rch & Prof#=Elm 01 00,Reach-1,5
Up Type=0
Dn Type=3
Dn Slope=0.005
Boundary for River Rch & Prof#=Elm 01 00,Reach-1,6
Up Type=0
Dn Type=3
Dn Slope=0.005
Boundary for River Rch & Prof#=Elm 01 00,Reach-1,7
Up Type=0
Dn Type=3
Dn Slope=0.005

--- Elm 01 00.g01 (geometry) ---

Geom Title=Existing Conditions

River Reach=Elm 01 00,Reach-1
Reach XY= 19
      1548705.00      6774288.00      1548716.17      6774298.87
      1548782.29      6774308.10      1548832.20      6774327.63
      1548847.39      6774353.67      1548853.91      6774379.71
      1548845.22      6774414.43      1548825.69      6774468.69
      1548814.84      6774512.09      1548808.33      6774603.23
      1548810.50      6774670.51      1548815.06      6774694.22
      1548848.86      6774735.83      1548857.50      6774781.97
      1548863.14      6774794.06      1548906.41      6774839.77
      1548949.67      6774885.49      1548955.07      6774906.12
      1548955.00      6774938.00

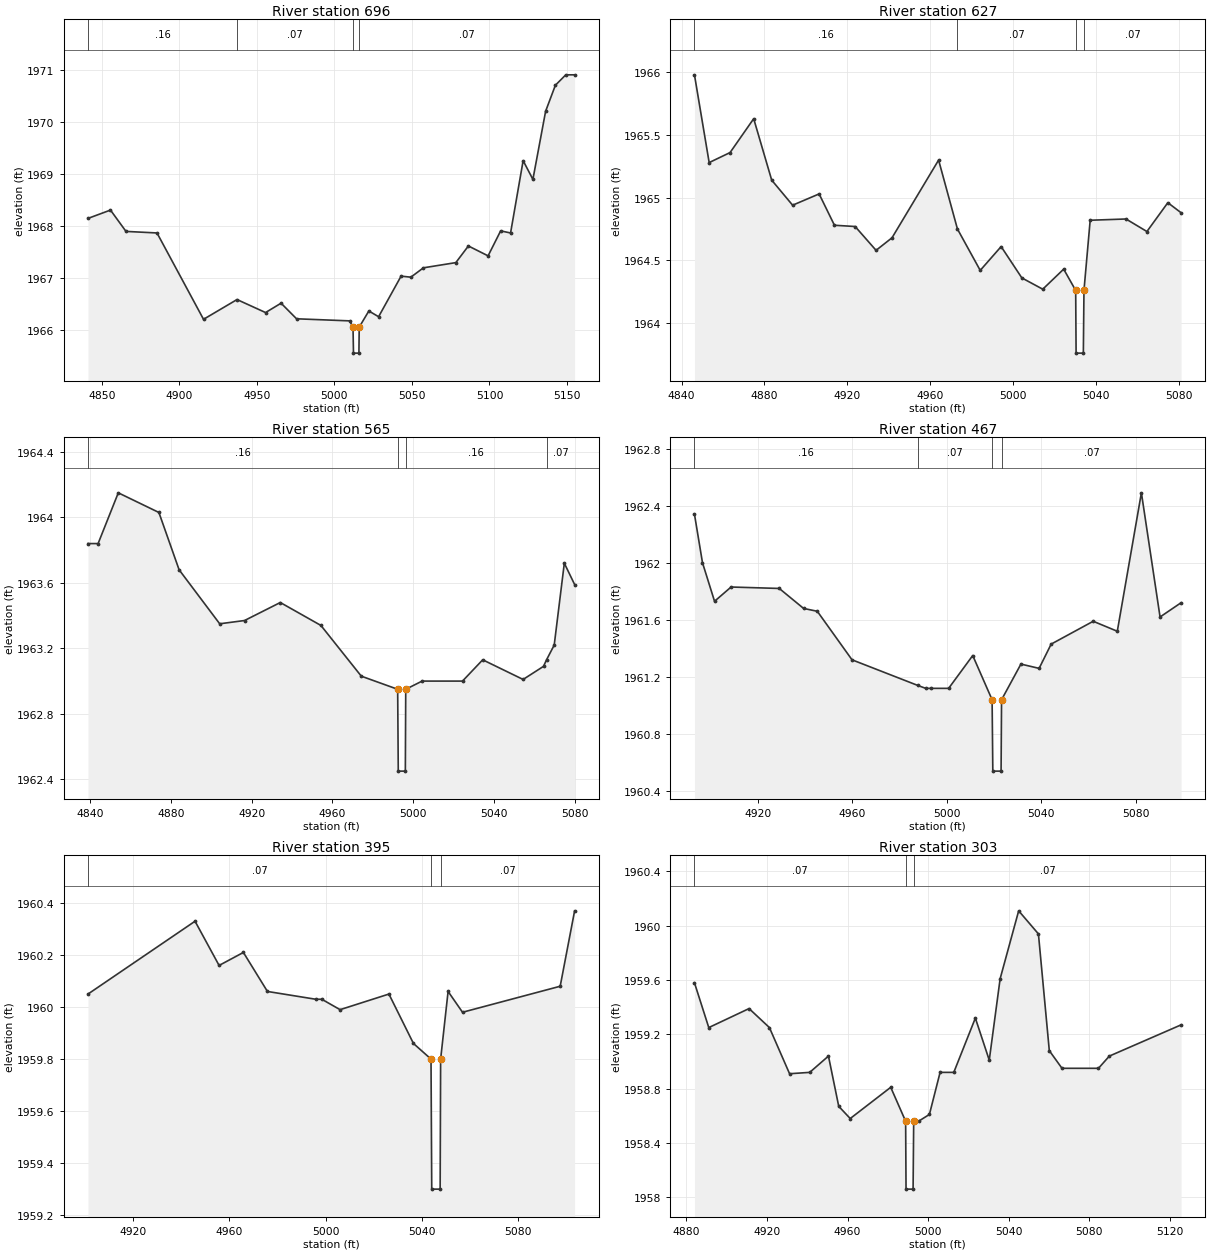
Type RM Length L Ch R = 1,696,69,69,69
BEGIN DESCRIPTION:
Elm 01 00 3972
END DESCRIPTION:
XS GIS Cut Line= 3
      1548650.47      6774320.83      1548819.15      6774318.56
      1548908.15      6774203.94
#Sta/Elev= 30
  4841.1 1968.14  4855.6 1968.30  4865.6 1967.89  4885.6 1967.86  4915.6 1966.20
  4937.2 1966.58  4955.6 1966.33  4965.6 1966.51  4975.6 1966.21  5009.8 1966.17
  5012.0 1966.05  5012.3 1965.55  5015.8 1965.55  5016.0 1966.05  5022.2 1966.36
  5028.5 1966.25  5043.0 1967.03  5049.3 1967.01  5057.4 1967.19  5078.3 1967.29
  5086.4 1967.61  5099.1 1967.42  5107.2 1967.90  5113.6 1967.86  5121.7 1969.25
  5128.0 1968.89  5136.2 1970.20  5142.5 1970.70  5149.2 1970.90  5154.9 1970.90
#Mann=4,-1,0
  4841.1    0.16       0  4937.2    0.07       0  5012.0    0.07       0
  5016.0    0.07       0
Bank Sta=5012,5016
Exp/Cntr=0.3,0.1

Type RM Length L Ch R = 1,627,62,62,62
BEGIN DESCRIPTION:
Elm 01 00 3974
END DESCRIPTION:
XS GIS Cut Line= 3
      1548698.00      6774369.64      1548755.35      6774377.43
      1548931.40      6774357.92
#Sta/Elev= 27
  4846.2 1965.98  4853.3 1965.28  4863.4 1965.36  4874.8 1965.63  4883.5 1965.14
  4893.6 1964.94  4906.4 1965.03  4913.8 1964.78  4923.8 1964.77  4933.9 1964.58
  4941.6 1964.68  4964.1 1965.30  4973.2 1964.75  4984.2 1964.42  4994.3 1964.61
  5004.3 1964.36  5014.4 1964.27  5024.5 1964.43  5030.3 1964.26  5030.5 1963.76
  5034.0 1963.76  5034.3 1964.26  5037.3 1964.82  5054.6 1964.83  5064.7 1964.73
  5074.8 1964.96  5081.2 1964.88
#Mann=4,-1,0
  4846.2    0.16       0  4973.2    0.07       0  5030.3    0.07       0
  5034.3    0.07       0
Bank Sta=5030.3,5034.3
Exp/Cntr=0.3,0.1

Type RM Length L Ch R = 1,565,98,98,98
BEGIN DESCRIPTION:
Elm 01 00 3973
END DESCRIPTION:
XS GIS Cut Line= 3
      1548680.01      6774426.35      1548757.32      6774432.04
      1548920.42      6774422.42
#Sta/Elev= 23
  4839.0 1963.84  4844.0 1963.84  4854.0 1964.15  4874.1 1964.03  4884.1 1963.68
  4904.2 1963.35  4916.5 1963.37  4934.2 1963.48  4954.3 1963.34  4974.3 1963.03
  4992.3 1962.95  4992.6 1962.45  4996.1 1962.45  4996.3 1962.95  5004.4 1963.00
  5024.4 1963.00  5034.4 1963.13  5054.4 1963.01  5064.5 1963.09  5066.0 1963.13
  5069.8 1963.22  5074.8 1963.72  5079.9 1963.59
#Mann=4,-1,0
  4839.0    0.16       0  4992.3    0.07       0  4996.3    0.16       0
  5066.0    0.07       0
Bank Sta=4992.3,4996.3
Exp/Cntr=0.3,0.1

Type RM Length L Ch R = 1,467,72,72,72
BEGIN DESCRIPTION:
Elm 01 00 3971
END DESCRIPTION:
XS GIS Cut Line= 3
      1548709.91      6774501.54      1548805.43      6774522.82
      1548911.51      6774501.82
#Sta/Elev= 25
  4893.2 1962.34  4896.6 1962.00  4901.7 1961.73  4908.7 1961.83  4929.1 1961.82
  4939.4 1961.68  4945.2 1961.66  4959.9 1961.32  4987.8 1961.14  4991.1 1961.12
  4993.4 1961.12  5000.8 1961.12  5011.0 1961.35  5019.2 1961.04  5019.5 1960.54
  5023.0 1960.54  5023.2 1961.04  5031.4 1961.29  5039.1 1961.26  5044.2 1961.43
  5062.0 1961.59  5072.2 1961.52  5082.4 1962.49  5090.3 1961.62  5099.2 1961.72
#Mann=4,-1,0
  4893.2    0.16       0  4987.8    0.07       0  5019.2    0.07       0
  5023.2    0.07       0
Bank Sta=5019.2,5023.2
Exp/Cntr=0.3,0.1

Type RM Length L Ch R = 1,395,92,92,92
BEGIN DESCRIPTION:
Elm 01 00 3970
END DESCRIPTION:
XS GIS Cut Line= 3
      1548710.55      6774587.51      1548805.11      6774592.95
      1548910.85      6774573.16
#Sta/Elev= 18
  4901.2 1960.05  4945.7 1960.33  4955.7 1960.16  4965.8 1960.21  4975.8 1960.06
  4995.9 1960.03  4998.4 1960.03  5006.0 1959.99  5026.3 1960.05  5036.5 1959.86
  5043.8 1959.80  5044.1 1959.30  5047.6 1959.30  5047.8 1959.80  5050.9 1960.06
  5056.9 1959.98  5097.5 1960.08  5103.5 1960.37
#Mann=3,-1,0
  4901.2    0.07       0  5043.8    0.07       0  5047.8    0.07       0
Bank Sta=5043.8,5047.8
Exp/Cntr=0.3,0.1

Type RM Length L Ch R = 1,303,64,64,64
BEGIN DESCRIPTION:
Elm 01 00 3969
END DESCRIPTION:
XS GIS Cut Line= 3
      1548697.97      6774676.95      1548808.75      6774686.45
      1548930.00      6774638.70
#Sta/Elev= 28
  4884.0 1959.58  4891.1 1959.25  4911.1 1959.39  4921.2 1959.25  4931.2 1958.91
  4941.2 1958.92  4950.5 1959.04  4955.6 1958.67  4961.3 1958.58  4981.4 1958.81
  4988.8 1958.56  4989.0 1958.06  4992.5 1958.06  4992.8 1958.56  4995.2 1958.56
  5000.6 1958.61  5005.9 1958.92  5012.7 1958.92  5023.4 1959.32  5030.3 1959.01
  5035.7 1959.61  5044.9 1960.11  5054.7 1959.94  5060.1 1959.08  5066.4 1958.95
  5084.5 1958.95  5089.9 1959.04  5125.5 1959.27
#Mann=3,-1,0
  4884.0    0.07       0  4988.8    0.07       0  4992.8    0.07       0
Bank Sta=4988.8,4992.8
Exp/Cntr=0.3,0.1

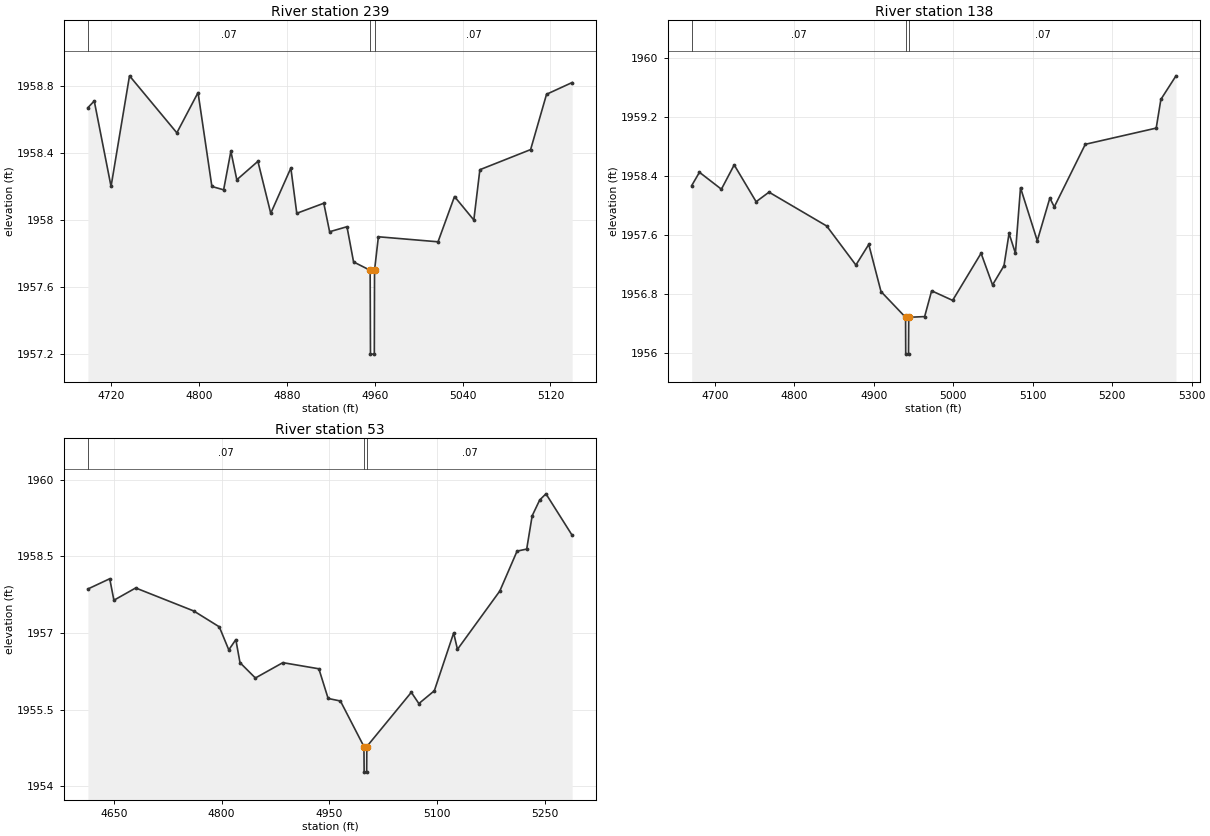
Type RM Length L Ch R = 1,239,101,101,101
BEGIN DESCRIPTION:
Elm 01 00 3968
END DESCRIPTION:
XS GIS Cut Line= 4
      1548569.63      6774685.71      1548780.37      6774766.97
      1548848.86      6774735.83      1548976.27      6774678.29
#Sta/Elev= 30
  4698.9 1958.67  4704.7 1958.71  4720.0 1958.20  4736.8 1958.86  4779.9 1958.52
  4799.2 1958.76  4811.8 1958.20  4822.5 1958.18  4829.1 1958.41  4834.5 1958.24
  4853.7 1958.35  4865.4 1958.04  4883.7 1958.31  4889.1 1958.04  4913.7 1958.10
  4919.0 1957.93  4934.8 1957.96  4940.8 1957.75  4955.9 1957.70  4956.2 1957.20
  4959.7 1957.20  4959.9 1957.70  4963.4 1957.90  5017.7 1957.87  5032.7 1958.14
  5050.3 1958.00  5055.8 1958.30  5102.0 1958.42  5116.5 1958.75  5139.8 1958.82
#Mann=3,-1,0
  4698.9    0.07       0  4955.9    0.07       0  4959.9    0.07       0
Bank Sta=4955.9,4959.9
Exp/Cntr=0.3,0.1

Type RM Length L Ch R = 1,138,85,85,85
BEGIN DESCRIPTION:
Elm 01 00 3967
END DESCRIPTION:
XS GIS Cut Line= 5
      1548595.69      6774716.10      1548824.05      6774839.83
      1548891.35      6774823.86      1548970.76      6774760.68
      1549051.39      6774601.07
#Sta/Elev= 30
  4671.1 1958.27  4680.8 1958.45  4708.4 1958.22  4724.5 1958.55  4752.1 1958.05
  4768.3 1958.18  4840.9 1957.72  4877.6 1957.19  4893.8 1957.47  4909.2 1956.83
  4940.1 1956.48  4940.3 1955.98  4943.8 1955.98  4944.1 1956.48  4964.1 1956.49
  4972.9 1956.84  4999.3 1956.71  5035.1 1957.35  5049.5 1956.92  5063.9 1957.18
  5070.3 1957.62  5078.3 1957.35  5084.7 1958.24  5105.8 1957.52  5121.6 1958.10
  5127.2 1957.98  5166.2 1958.83  5255.4 1959.05  5261.3 1959.44  5280.3 1959.76
#Mann=3,-1,0
  4671.1    0.07       0  4940.1    0.07       0  4944.1    0.07       0
Bank Sta=4940.1,4944.1
Exp/Cntr=0.3,0.1

Type RM Length L Ch R = 1,53,0,0,0
BEGIN DESCRIPTION:
Elm 01 00 3966
END DESCRIPTION:
XS GIS Cut Line= 5
      1548597.79      6774755.12      1548806.16      6774878.84
      1548949.67      6774885.49      1548989.90      6774843.52
      1549060.04      6774625.04
#Sta/Elev= 30
  4614.0 1957.86  4644.4 1958.06  4650.2 1957.64  4680.5 1957.88  4761.3 1957.43
  4796.8 1957.12  4810.0 1956.67  4819.8 1956.87  4825.6 1956.42  4847.0 1956.12
  4885.2 1956.42  4935.3 1956.30  4948.2 1955.72  4965.3 1955.67  4998.0 1954.78
  4998.3 1954.28  5001.8 1954.28  5002.0 1954.78  5063.9 1955.84  5074.4 1955.62
  5095.9 1955.87  5122.8 1957.00  5128.1 1956.68  5187.0 1957.82  5211.0 1958.60
  5224.4 1958.64  5232.0 1959.29  5242.5 1959.60  5251.2 1959.72  5287.6 1958.91
#Mann=3,-1,0
  4614.0    0.07       0  4998.0    0.07       0  5002.0    0.07       0
Bank Sta=4998,5002
Exp/Cntr=0.3,0.1

Chan Stop Cuts=-1