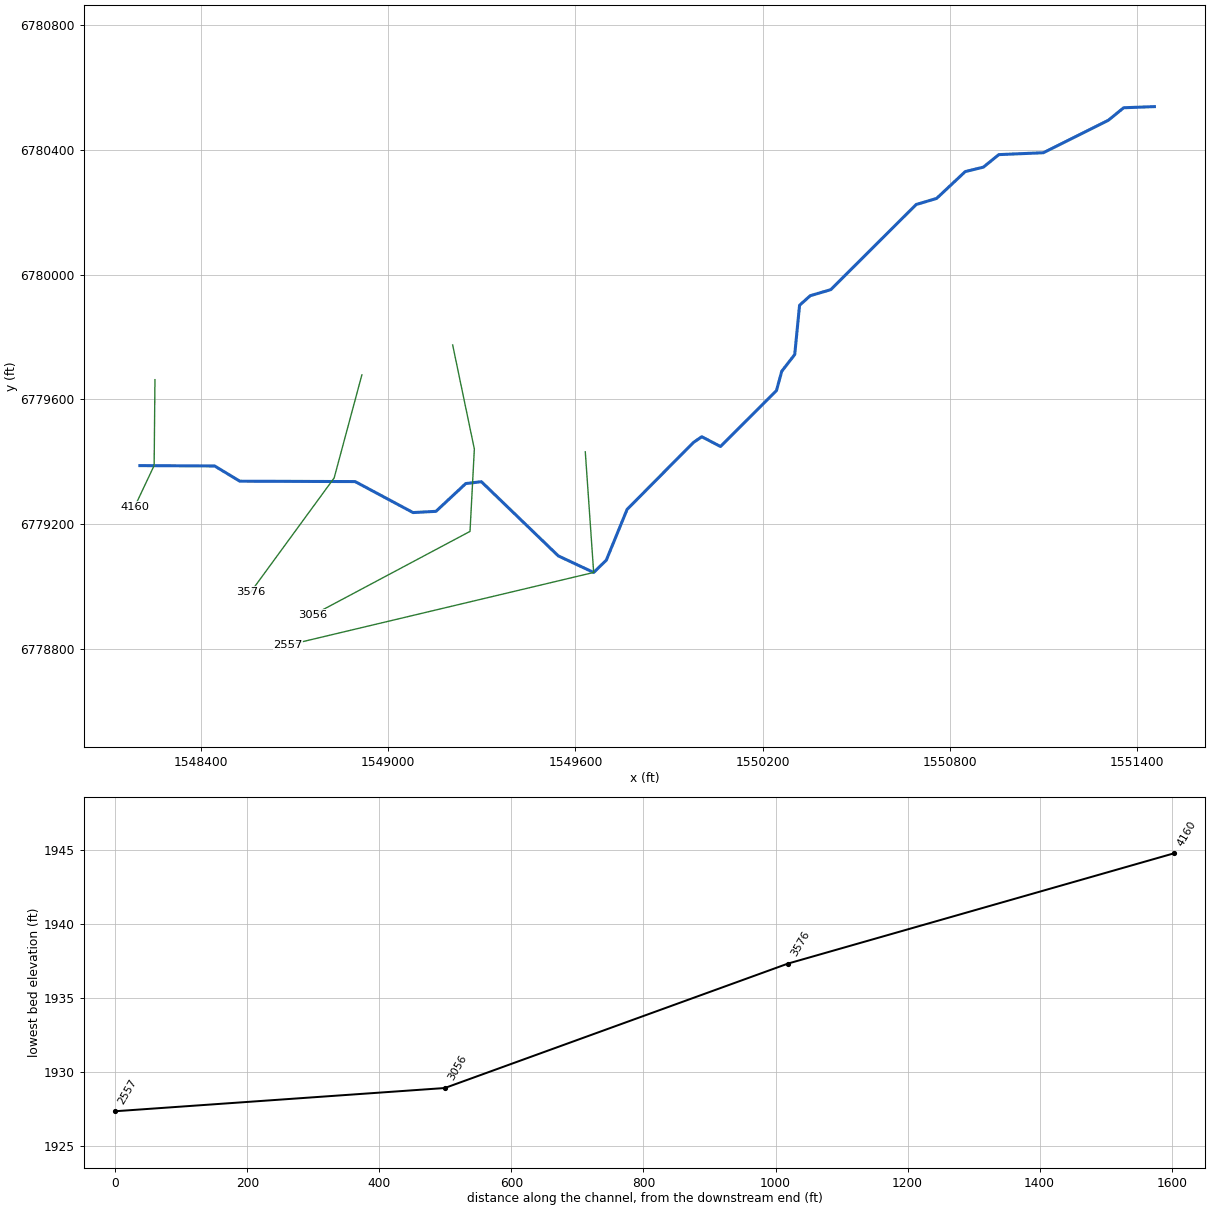
--- Elm 01 01.prj (project) ---

Proj Title=Elm 01 01 Base Level Engineering
Current Plan=p01
Default Exp/Contr=0.3,0.1
English Units
Geom File=g01
Flow File=f01
Plan File=p01
BEGIN DESCRIPTION:
Elm 01 01
END DESCRIPTION:

--- Elm 01 01.p01 (plan) ---

Plan Title=Multiple Run
Short Identifier=Multiple
Geom File=g01
Flow File=f01
Subcritical Flow
K Sum by GR= 0
Std Step Tol= 0.01
Critical Tol= 0.01
Num of Std Step Trials= 20
Max Error Tol= 0.3
Flow Tol Ratio= 0.001
Split Flow NTrial= 30
Split Flow Tol= 0.02
Split Flow Ratio= 0.02
Log Output Level= 0
Friction Slope Method= 1
Unsteady Friction Slope Method= 2
Unsteady Bridges Friction Slope Method= 1
Parabolic Critical Depth
Global Vel Dist=  1 , 1 , 1
Global Log Level= 0
CheckData=True
Encroach Param= -1, 0, 0, 0
BEGIN DESCRIPTION:
Multiple Run
END DESCRIPTION:

--- Elm 01 01.f01 (steady flow) ---

Flow Title=Multiple
Number of Profiles=7
Profile Names=10-year,25-year,50-year,1pct_min,100-year,1pct_plu,500-year
River Rch & RM= Elm 01 01,Reach-1,4160
     213     294     360     274     440     605     664
Boundary for River Rch & Prof#=Elm 01 01,Reach-1,1
Up Type=0
Dn Type=3
Dn Slope=0.005
Boundary for River Rch & Prof#=Elm 01 01,Reach-1,2
Up Type=0
Dn Type=3
Dn Slope=0.005
Boundary for River Rch & Prof#=Elm 01 01,Reach-1,3
Up Type=0
Dn Type=3
Dn Slope=0.005
Boundary for River Rch & Prof#=Elm 01 01,Reach-1,4
Up Type=0
Dn Type=3
Dn Slope=0.005
Boundary for River Rch & Prof#=Elm 01 01,Reach-1,5
Up Type=0
Dn Type=3
Dn Slope=0.005
Boundary for River Rch & Prof#=Elm 01 01,Reach-1,6
Up Type=0
Dn Type=3
Dn Slope=0.005
Boundary for River Rch & Prof#=Elm 01 01,Reach-1,7
Up Type=0
Dn Type=3
Dn Slope=0.005

--- Elm 01 01.g01 (geometry) ---

Geom Title=Existing Conditions

River Reach=Elm 01 01,Reach-1
Reach XY= 30
      1548205.00      6779388.00      1548444.50      6779386.78
      1548525.03      6779338.07      1548894.50      6779336.80
      1549080.00      6779237.58      1549153.50      6779241.47
      1549248.96      6779330.52      1549298.95      6779336.42
      1549545.32      6779098.75      1549658.66      6779045.67
      1549699.17      6779085.14      1549765.76      6779247.68
      1549978.33      6779462.23      1550005.00      6779480.44
      1550065.00      6779449.24      1550244.24      6779628.32
      1550261.14      6779690.17      1550302.75      6779743.93
      1550318.23      6779901.67      1550352.43      6779932.26
      1550418.20      6779951.64      1550691.79      6780224.37
      1550757.28      6780243.87      1550848.95      6780329.84
      1550907.17      6780344.14      1550956.56      6780384.24
      1551099.07      6780390.25      1551307.19      6780494.09
      1551356.50      6780534.37      1551455.00      6780538.00

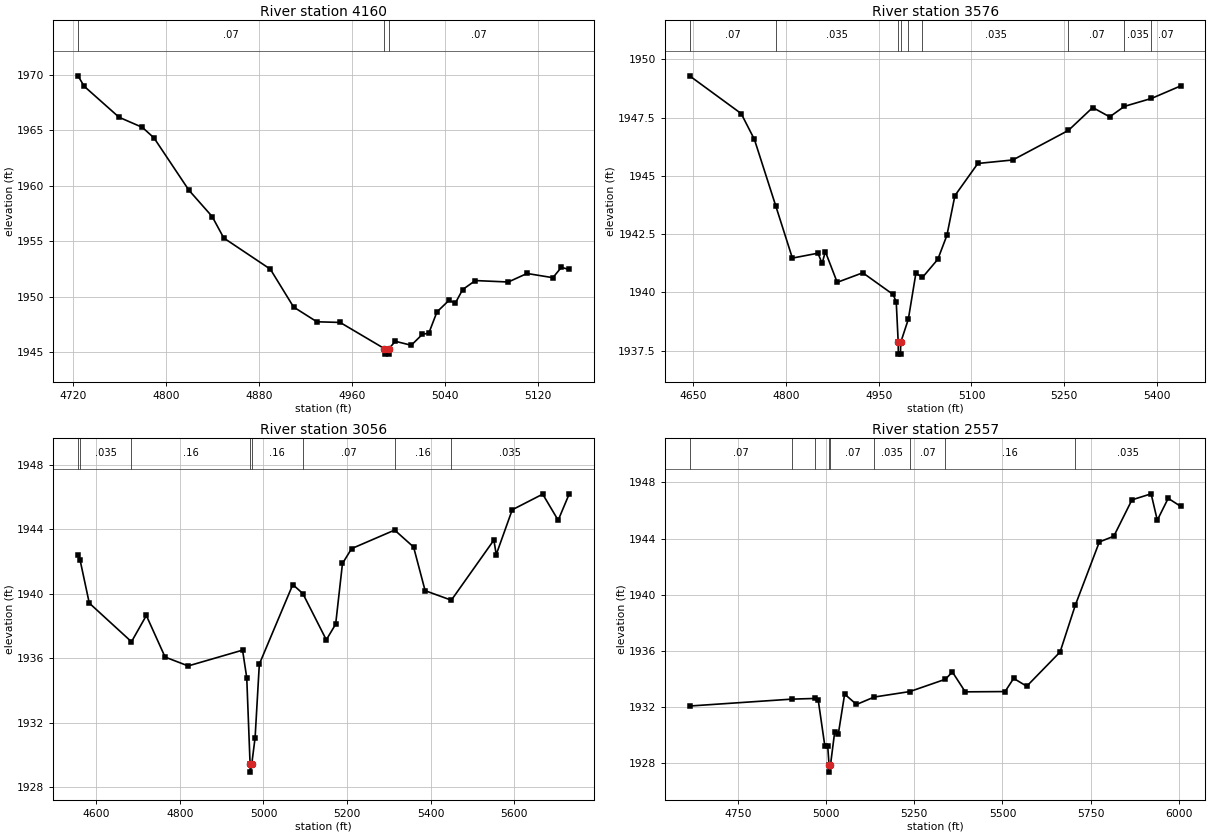
Type RM Length L Ch R = 1,4160,584,584,584
BEGIN DESCRIPTION:
406
END DESCRIPTION:
XS GIS Cut Line= 3
      1548253.26      6779663.31      1548250.66      6779388.22
      1548187.84      6779255.21
#Sta/Elev= 30
  4724.4 1969.92  4729.7 1968.98  4759.7 1966.18  4779.7 1965.27  4789.7 1964.32
  4819.7 1959.60  4839.7 1957.22  4849.7 1955.28  4889.7 1952.47  4909.7 1949.05
  4929.7 1947.72  4949.7 1947.66  4987.7 1945.30  4988.0 1944.80  4991.5 1944.80
  4991.7 1945.30  4997.1 1945.96  5010.8 1945.60  5020.4 1946.59  5025.9 1946.69
  5032.9 1948.61  5043.2 1949.65  5048.7 1949.41  5055.0 1950.63  5065.9 1951.44
  5094.2 1951.31  5110.3 1952.08  5132.5 1951.70  5139.8 1952.63  5146.6 1952.44
#Mann=3,-1,0
  4724.4    0.07       0  4987.7    0.07       0  4991.7    0.07       0
Bank Sta=4987.7,4991.7
Exp/Cntr=0.3,0.1

Type RM Length L Ch R = 1,3576,520,520,520
BEGIN DESCRIPTION:
827
END DESCRIPTION:
XS GIS Cut Line= 3
      1548916.09      6779678.59      1548827.33      6779348.53
      1548560.02      6778982.92
#Sta/Elev= 30
  4644.0 1949.29  4727.5 1947.67  4748.9 1946.56  4783.4 1943.71  4810.3 1941.47
  4851.7 1941.68  4858.4 1941.24  4863.6 1941.75  4882.8 1940.43  4924.2 1940.84
  4973.2 1939.91  4978.3 1939.59  4981.5 1937.85  4981.7 1937.35  4985.2 1937.35
  4985.5 1937.85  4997.9 1938.85  5010.1 1940.82  5020.7 1940.64  5045.6 1941.42
  5060.3 1942.45  5073.2 1944.15  5110.3 1945.53  5166.9 1945.68  5256.9 1946.95
  5296.1 1947.93  5323.6 1947.53  5347.4 1947.98  5391.2 1948.32  5438.7 1948.86
#Mann=9,-1,0
  4644.0    0.07       0  4783.4   0.035       0  4981.5    0.07       0
  4985.5   0.035       0  4997.9    0.07       0  5020.7   0.035       0
  5256.9    0.07       0  5347.4   0.035       0  5391.2    0.07       0
Bank Sta=4981.5,4985.5
Exp/Cntr=0.3,0.1

Type RM Length L Ch R = 1,3056,499,499,499
BEGIN DESCRIPTION:
875
END DESCRIPTION:
XS GIS Cut Line= 4
      1549206.96      6779774.47      1549276.41      6779441.13
      1549262.52      6779177.24      1548758.93      6778909.27
#Sta/Elev= 30
  4556.3 1942.42  4561.5 1942.07  4583.3 1939.42  4684.3 1937.02  4719.8 1938.65
  4764.7 1936.07  4819.9 1935.52  4950.0 1936.50  4960.0 1934.79  4968.0 1929.43
  4968.3 1928.93  4972.0 1929.43  4980.0 1931.07  4990.1 1935.63  5070.2 1940.57
  5094.2 1940.01  5150.3 1937.14  5172.7 1938.11  5189.0 1941.88  5210.9 1942.80
  5313.8 1943.95  5359.1 1942.90  5386.7 1940.19  5449.4 1939.60  5551.2 1943.33
  5556.8 1942.43  5595.1 1945.21  5668.0 1946.18  5705.0 1944.56  5731.5 1946.20
#Mann=8,-1,0
  4556.3   0.063       0  4561.5   0.035       0  4684.3    0.16       0
  4968.0    0.07       0  4972.0    0.16       0  5094.2    0.07       0
  5313.8    0.16       0  5449.4   0.035       0
Bank Sta=4968,4972
Exp/Cntr=0.3,0.1

Type RM Length L Ch R = 1,2557,0,0,0
BEGIN DESCRIPTION:
405
END DESCRIPTION:
XS GIS Cut Line= 3
      1549631.82      6779432.14      1549658.66      6779045.67
      1548680.03      6778813.01
#Sta/Elev= 30
  4612.6 1932.07  4901.8 1932.56  4968.6 1932.61  4977.6 1932.47  4996.3 1929.21
  5004.4 1929.21  5008.2 1927.86  5008.5 1927.36  5012.2 1927.86  5024.3 1930.25
  5034.6 1930.10  5052.4 1932.92  5086.0 1932.18  5136.2 1932.71  5237.2 1933.10
  5338.3 1933.98  5357.9 1934.50  5394.4 1933.08  5507.4 1933.10  5531.7 1934.04
  5568.8 1933.48  5663.4 1935.92  5706.5 1939.25  5774.7 1943.76  5815.8 1944.17
  5867.2 1946.76  5921.6 1947.19  5939.1 1945.31  5970.0 1946.87  6005.9 1946.29
#Mann=9,-1,0
  4612.6    0.07       0  4901.8    0.16       0  4968.6    0.07       0
  5008.2    0.07       0  5012.2    0.07       0  5136.2   0.035       0
  5237.2    0.07       0  5338.3    0.16       0  5706.5   0.035       0
Bank Sta=5008.2,5012.2
Exp/Cntr=0.3,0.1

Chan Stop Cuts=-1