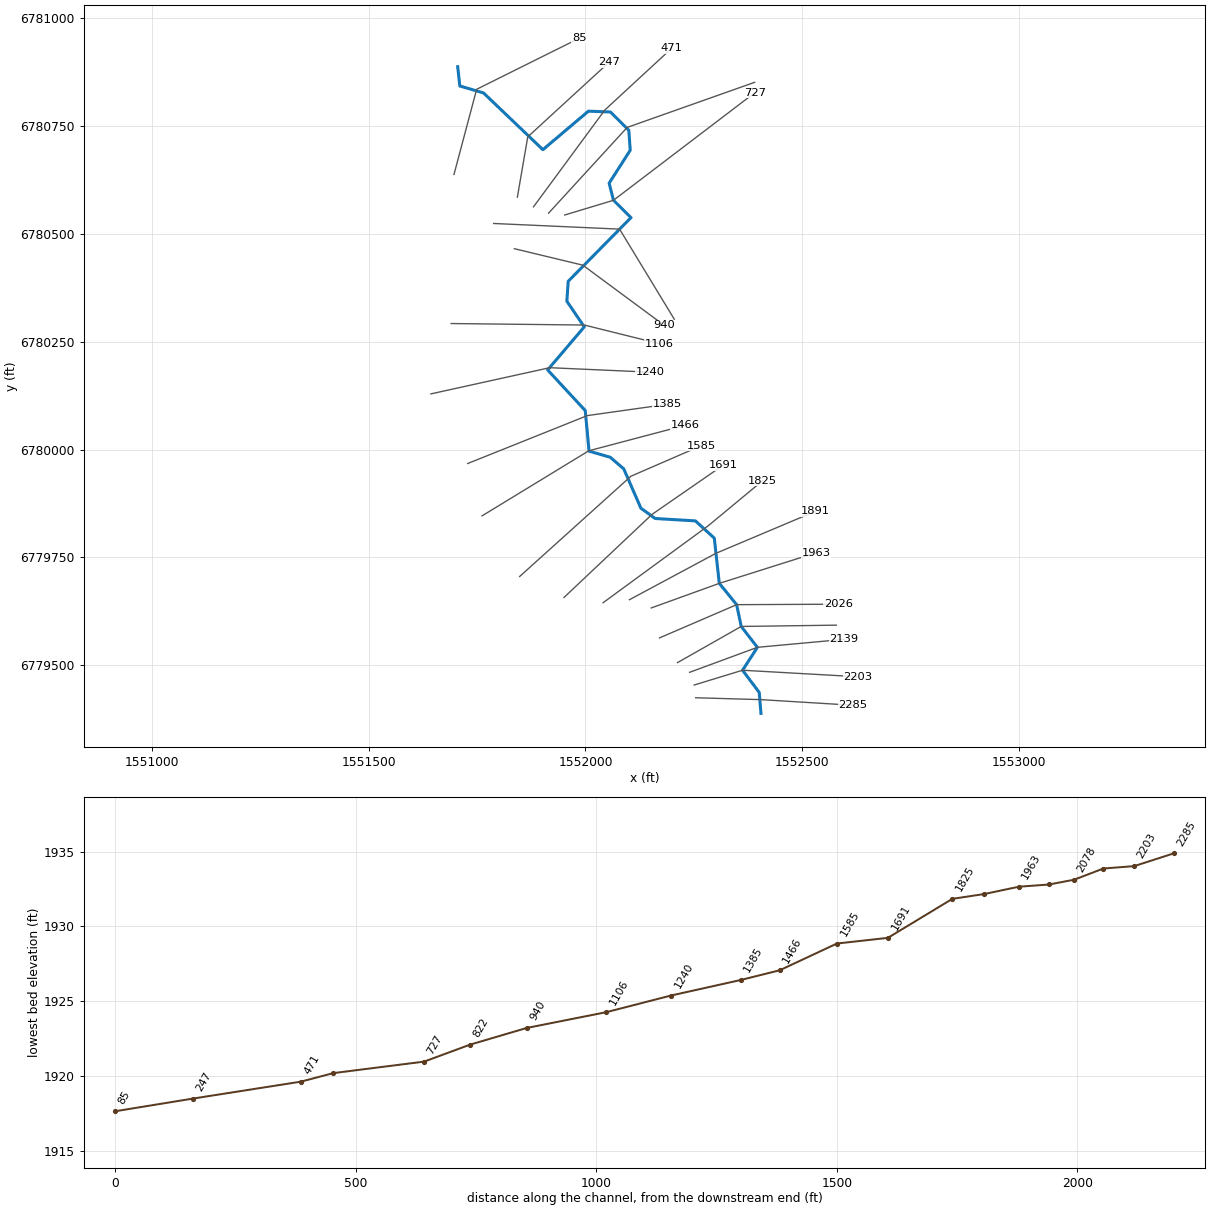
--- Elm 01 02.prj (project) ---

Proj Title=Elm 01 02 Base Level Engineering
Current Plan=p01
Default Exp/Contr=0.3,0.1
English Units
Geom File=g01
Flow File=f01
Plan File=p01
BEGIN DESCRIPTION:
Elm 01 02
END DESCRIPTION:

--- Elm 01 02.p01 (plan) ---

Plan Title=Multiple Run
Short Identifier=Multiple
Geom File=g01
Flow File=f01
Subcritical Flow
K Sum by GR= 0
Std Step Tol= 0.01
Critical Tol= 0.01
Num of Std Step Trials= 20
Max Error Tol= 0.3
Flow Tol Ratio= 0.001
Split Flow NTrial= 30
Split Flow Tol= 0.02
Split Flow Ratio= 0.02
Log Output Level= 0
Friction Slope Method= 1
Unsteady Friction Slope Method= 2
Unsteady Bridges Friction Slope Method= 1
Parabolic Critical Depth
Global Vel Dist=  1 , 1 , 1
Global Log Level= 0
CheckData=True
Encroach Param= -1, 0, 0, 0
BEGIN DESCRIPTION:
Multiple Run
END DESCRIPTION:

--- Elm 01 02.f01 (steady flow) ---

Flow Title=Multiple
Number of Profiles=7
Profile Names=10-year,25-year,50-year,1pct_min,100-year,1pct_plu,500-year
River Rch & RM= Elm 01 02,Reach-1,2285
     126     168     202     151     242     332     349
River Rch & RM= Elm 01 02,Reach-1,727
     146     196     236     177     284     391     415
Boundary for River Rch & Prof#=Elm 01 02,Reach-1,1
Up Type=0
Dn Type=3
Dn Slope=0.005
Boundary for River Rch & Prof#=Elm 01 02,Reach-1,2
Up Type=0
Dn Type=3
Dn Slope=0.005
Boundary for River Rch & Prof#=Elm 01 02,Reach-1,3
Up Type=0
Dn Type=3
Dn Slope=0.005
Boundary for River Rch & Prof#=Elm 01 02,Reach-1,4
Up Type=0
Dn Type=3
Dn Slope=0.005
Boundary for River Rch & Prof#=Elm 01 02,Reach-1,5
Up Type=0
Dn Type=3
Dn Slope=0.005
Boundary for River Rch & Prof#=Elm 01 02,Reach-1,6
Up Type=0
Dn Type=3
Dn Slope=0.005
Boundary for River Rch & Prof#=Elm 01 02,Reach-1,7
Up Type=0
Dn Type=3
Dn Slope=0.005

--- Elm 01 02.g01 (geometry) ---

Geom Title=Existing Conditions

River Reach=Elm 01 02,Reach-1
Reach XY= 30
      1552405.00      6779388.00      1552401.02      6779436.64
      1552362.57      6779488.06      1552396.78      6779541.23
      1552359.41      6779589.63      1552348.91      6779640.17
      1552308.83      6779689.59      1552297.27      6779794.50
      1552253.74      6779834.48      1552160.72      6779840.08
      1552127.82      6779864.05      1552088.41      6779955.00
      1552057.15      6779982.08      1552008.19      6779996.35
      1551999.42      6780090.37      1551912.62      6780184.67
      1551997.15      6780284.59      1551956.99      6780344.05
      1551960.11      6780390.29      1552105.00      6780538.00
      1552064.62      6780578.20      1552054.57      6780617.89
      1552103.22      6780694.17      1552100.01      6780740.62
      1552057.61      6780783.04      1552006.68      6780784.89
      1551901.66      6780695.60      1551764.54      6780827.28
      1551709.92      6780843.33      1551705.00      6780888.00

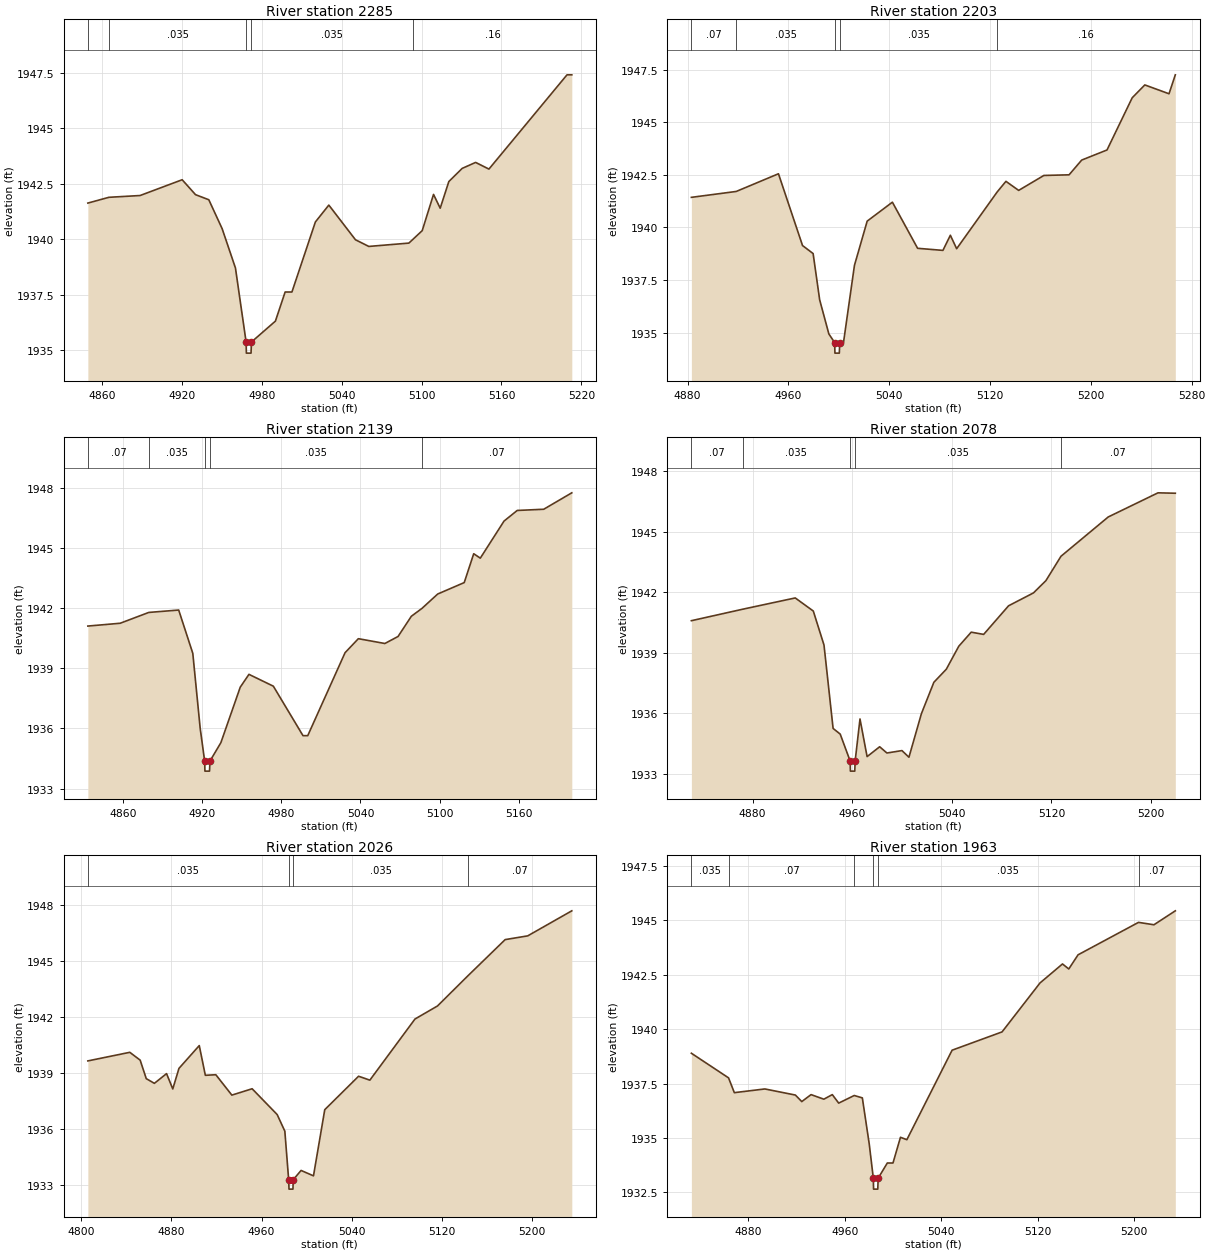
Type RM Length L Ch R = 1,2285,82,82,82
BEGIN DESCRIPTION:
Elm 01 02 3855
END DESCRIPTION:
XS GIS Cut Line= 3
      1552254.26      6779424.24      1552404.70      6779419.88
      1552617.10      6779406.87
#Sta/Elev= 30
  4849.5 1941.63  4865.3 1941.89  4888.7 1941.97  4920.3 1942.68  4930.3 1942.01
  4940.3 1941.78  4950.3 1940.48  4960.3 1938.71  4968.3 1935.38  4968.5 1934.88
  4972.0 1934.88  4972.3 1935.38  4990.3 1936.32  4997.6 1937.63  5002.7 1937.63
  5020.3 1940.78  5030.4 1941.54  5050.4 1939.98  5060.4 1939.68  5090.5 1939.83
  5093.9 1940.02  5100.5 1940.39  5109.0 1942.02  5114.0 1941.40  5120.5 1942.60
  5130.5 1943.19  5140.6 1943.46  5150.6 1943.16  5209.2 1947.40  5212.8 1947.40
#Mann=5,-1,0
  4849.5    0.07       0  4865.3   0.035       0  4968.3   0.035       0
  4972.3   0.035       0  5093.9    0.16       0
Bank Sta=4968.3,4972.3
Exp/Cntr=0.3,0.1

Type RM Length L Ch R = 1,2203,64,64,64
BEGIN DESCRIPTION:
Elm 01 02 3857
END DESCRIPTION:
XS GIS Cut Line= 3
      1552250.72      6779453.74      1552362.57      6779488.06
      1552629.14      6779472.95
#Sta/Elev= 30
  4883.0 1941.43  4918.6 1941.71  4952.1 1942.55  4971.2 1939.14  4979.6 1938.76
  4984.8 1936.56  4992.1 1934.94  4996.7 1934.53  4996.9 1934.03  5000.4 1934.03
  5000.7 1934.53  5003.7 1934.53  5012.4 1938.20  5022.5 1940.30  5042.5 1941.20
  5062.5 1939.01  5082.6 1938.91  5088.5 1939.63  5093.5 1938.99  5125.7 1941.69
  5132.6 1942.19  5142.7 1941.76  5162.7 1942.47  5182.7 1942.50  5192.7 1943.20
  5212.8 1943.68  5232.8 1946.16  5242.8 1946.77  5262.0 1946.35  5267.0 1947.25
#Mann=5,-1,0
  4883.0    0.07       0  4918.6   0.035       0  4996.7   0.035       0
  5000.7   0.035       0  5125.7    0.16       0
Bank Sta=4996.7,5000.7
Exp/Cntr=0.3,0.1

Type RM Length L Ch R = 1,2139,61,61,61
BEGIN DESCRIPTION:
Elm 01 02 3853
END DESCRIPTION:
XS GIS Cut Line= 3
      1552240.37      6779483.27      1552396.78      6779541.23
      1552596.23      6779559.65
#Sta/Elev= 30
  4833.2 1941.11  4857.7 1941.25  4879.4 1941.79  4902.1 1941.91  4912.8 1939.75
  4918.4 1936.01  4921.8 1934.37  4922.0 1933.87  4925.5 1933.87  4925.8 1934.37
  4934.1 1935.29  4948.8 1938.06  4955.4 1938.70  4973.9 1938.11  4996.4 1935.64
  5000.0 1935.64  5028.3 1939.78  5038.4 1940.48  5058.5 1940.24  5068.5 1940.59
  5078.6 1941.60  5086.6 1941.99  5098.6 1942.71  5118.7 1943.28  5125.9 1944.72
  5130.9 1944.50  5148.9 1946.35  5158.9 1946.88  5179.0 1946.94  5200.3 1947.76
#Mann=5,-1,0
  4833.2    0.07       0  4879.4   0.035       0  4921.8   0.035       0
  4925.8   0.035       0  5086.6    0.07       0
Bank Sta=4921.8,4925.8
Exp/Cntr=0.3,0.1

Type RM Length L Ch R = 1,2078,52,52,52
BEGIN DESCRIPTION:
Elm 01 02 3851
END DESCRIPTION:
XS GIS Cut Line= 3
      1552212.54      6779505.82      1552359.41      6779589.63
      1552578.89      6779592.64
#Sta/Elev= 30
  4830.9 1940.59  4872.1 1941.16  4914.3 1941.72  4928.8 1941.07  4937.4 1939.38
  4944.7 1935.24  4950.4 1934.96  4958.4 1933.62  4958.6 1933.12  4962.1 1933.12
  4962.4 1933.62  4966.3 1935.71  4972.0 1933.84  4982.1 1934.33  4987.9 1934.02
  5000.0 1934.14  5005.6 1933.81  5015.6 1935.97  5025.6 1937.53  5035.6 1938.18
  5045.6 1939.32  5055.6 1940.02  5065.6 1939.91  5085.6 1941.33  5105.6 1941.97
  5115.6 1942.58  5127.7 1943.79  5165.6 1945.74  5205.6 1946.94  5219.5 1946.92
#Mann=5,-1,0
  4830.9    0.07       0  4872.1   0.035       0  4958.4   0.035       0
  4962.4   0.035       0  5127.7    0.07       0
Bank Sta=4958.4,4962.4
Exp/Cntr=0.3,0.1

Type RM Length L Ch R = 1,2026,63,63,63
BEGIN DESCRIPTION:
Elm 01 02 3849
END DESCRIPTION:
XS GIS Cut Line= 3
      1552170.87      6779563.11      1552348.91      6779640.17
      1552584.11      6779641.25
#Sta/Elev= 30
  4806.0 1939.66  4843.2 1940.12  4852.4 1939.70  4857.8 1938.71  4865.0 1938.46
  4875.8 1938.98  4881.3 1938.16  4886.8 1939.26  4904.8 1940.48  4910.2 1938.89
  4919.5 1938.92  4933.7 1937.83  4951.7 1938.17  4973.9 1936.79  4980.7 1935.90
  4984.1 1933.30  4984.4 1932.80  4987.9 1932.80  4988.1 1933.30  4995.1 1933.80
  5006.1 1933.51  5016.1 1937.05  5046.1 1938.84  5056.1 1938.63  5096.1 1941.90
  5116.1 1942.60  5143.0 1944.21  5176.1 1946.15  5196.1 1946.35  5235.2 1947.69
#Mann=4,-1,0
  4806.0   0.035       0  4984.1   0.035       0  4988.1   0.035       0
  5143.0    0.07       0
Bank Sta=4984.1,4988.1
Exp/Cntr=0.3,0.1

Type RM Length L Ch R = 1,1963,72,72,72
BEGIN DESCRIPTION:
Elm 01 02 1962.567
END DESCRIPTION:
XS GIS Cut Line= 3
      1552151.77      6779632.56      1552308.83      6779689.59
      1552531.85      6779760.44
#Sta/Elev= 30
  4832.9 1938.89  4863.7 1937.76  4868.5 1937.08  4893.8 1937.25  4919.1 1936.97
  4924.4 1936.67  4932.1 1936.99  4942.7 1936.78  4949.7 1936.99  4955.0 1936.60
  4967.9 1936.95  4974.6 1936.84  4980.3 1934.73  4983.7 1933.15  4983.9 1932.65
  4987.4 1932.65  4987.7 1933.15  4995.3 1933.85  5000.0 1933.85  5006.2 1935.03
  5011.5 1934.92  5049.0 1939.03  5090.4 1939.87  5121.9 1942.12  5140.5 1942.99
  5145.7 1942.76  5153.4 1943.41  5203.5 1944.90  5216.3 1944.79  5234.0 1945.43
#Mann=6,-1,0
  4832.9   0.035       0  4863.7    0.07       0  4967.9   0.035       0
  4983.7   0.035       0  4987.7   0.035       0  5203.5    0.07       0
Bank Sta=4983.7,4987.7
Exp/Cntr=0.3,0.1

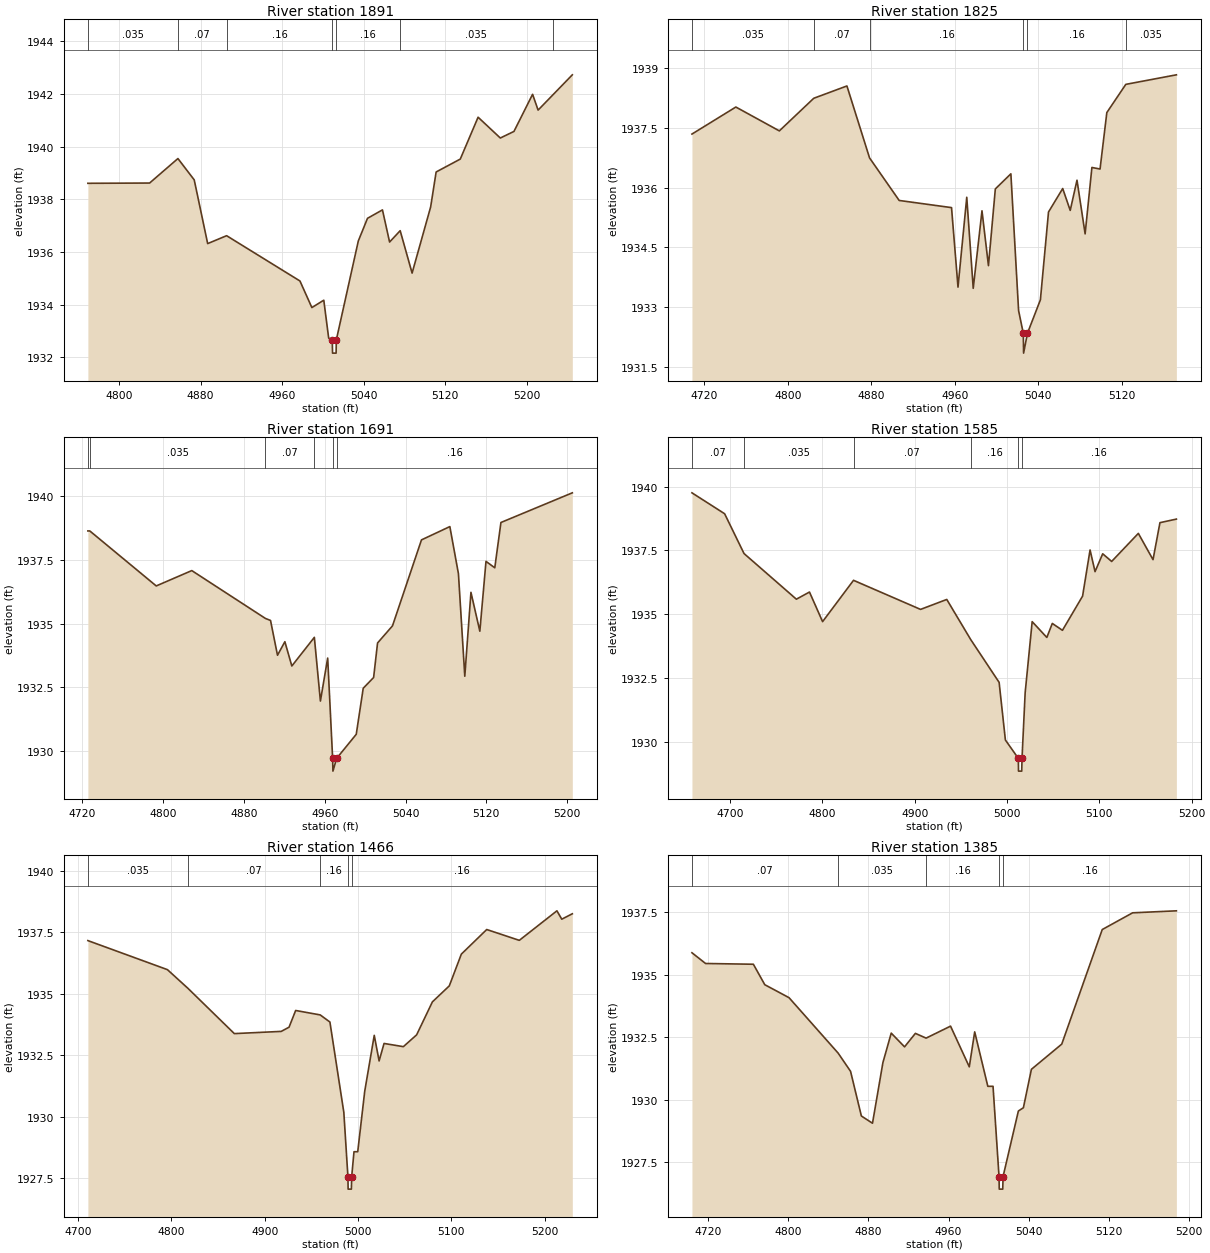
Type RM Length L Ch R = 1,1891,66,66,66
BEGIN DESCRIPTION:
Elm 01 02 1890.99
END DESCRIPTION:
XS GIS Cut Line= 3
      1552101.44      6779651.66      1552301.11      6779759.31
      1552530.12      6779856.46
#Sta/Elev= 30
  4769.3 1938.61  4829.9 1938.62  4857.7 1939.55  4873.7 1938.74  4886.9 1936.32
  4905.5 1936.62  4977.5 1934.90  4989.2 1933.89  5000.9 1934.17  5005.7 1932.73
  5009.2 1932.66  5009.5 1932.16  5013.0 1932.16  5013.2 1932.66  5034.8 1936.42
  5043.8 1937.28  5058.5 1937.60  5065.5 1936.38  5075.9 1936.81  5087.6 1935.20
  5105.8 1937.71  5111.2 1939.04  5134.9 1939.53  5152.4 1941.12  5174.2 1940.33
  5187.6 1940.58  5205.9 1941.99  5211.3 1941.39  5225.6 1941.96  5244.9 1942.73
#Mann=7,-1,0
  4769.3   0.035       0  4857.7    0.07       0  4905.5    0.16       0
  5009.2    0.07       0  5013.2    0.16       0  5075.9   0.035       0
  5225.6    0.07       0
Bank Sta=5009.2,5013.2
Exp/Cntr=0.3,0.1

Type RM Length L Ch R = 1,1825,134,134,134
BEGIN DESCRIPTION:
Elm 01 02 1824.52
END DESCRIPTION:
XS GIS Cut Line= 3
      1552040.67      6779644.71      1552283.75      6779823.54
      1552408.76      6779927.71
#Sta/Elev= 30
  4708.0 1937.35  4750.1 1938.03  4791.8 1937.43  4824.8 1938.25  4856.6 1938.56
  4878.3 1936.75  4906.7 1935.68  4956.9 1935.50  4963.1 1933.50  4971.5 1935.76
  4977.7 1933.47  4986.1 1935.42  4992.3 1934.04  4998.9 1935.97  5013.8 1936.35
  5021.2 1932.91  5025.7 1932.34  5026.0 1931.84  5029.7 1932.34  5042.1 1933.18
  5049.9 1935.39  5063.5 1935.98  5070.7 1935.43  5077.2 1936.19  5085.0 1934.84
  5091.5 1936.51  5099.3 1936.47  5105.8 1937.89  5124.0 1938.60  5172.5 1938.84
#Mann=6,-1,0
  4708.0   0.035       0  4824.8    0.07       0  4878.3    0.16       0
  5025.7    0.07       0  5029.7    0.16       0  5124.0   0.035       0
Bank Sta=5025.7,5029.7
Exp/Cntr=0.3,0.1

Type RM Length L Ch R = 1,1691,106,106,106
BEGIN DESCRIPTION:
Elm 01 02 1690.79
END DESCRIPTION:
XS GIS Cut Line= 3
      1551950.44      6779656.90      1552153.54      6779849.58
      1552317.66      6779963.60
#Sta/Elev= 30
  4725.4 1938.62  4727.3 1938.62  4793.1 1936.47  4828.3 1937.07  4901.2 1935.20
  4906.3 1935.12  4913.2 1933.76  4920.5 1934.29  4927.4 1933.34  4949.7 1934.46
  4955.7 1931.97  4962.9 1933.65  4967.8 1929.73  4968.1 1929.23  4971.8 1929.73
  4991.2 1930.67  4998.1 1932.47  5008.4 1932.89  5012.3 1934.24  5027.1 1934.91
  5055.8 1938.27  5083.9 1938.79  5092.4 1936.95  5098.7 1932.94  5104.8 1936.22
  5113.6 1934.70  5119.7 1937.43  5128.4 1937.18  5134.5 1938.95  5205.2 1940.11
#Mann=6,-1,0
  4725.4    0.07       0  4727.3   0.035       0  4901.2    0.07       0
  4949.7    0.16       0  4967.8    0.07       0  4971.8    0.16       0
Bank Sta=4967.8,4971.8
Exp/Cntr=0.3,0.1

Type RM Length L Ch R = 1,1585,119,119,119
BEGIN DESCRIPTION:
Elm 01 02 1584.56
END DESCRIPTION:
XS GIS Cut Line= 3
      1551847.98      6779705.48      1552104.93      6779938.13
      1552268.15      6780009.32
#Sta/Elev= 30
  4658.7 1939.76  4694.1 1938.94  4715.1 1937.38  4771.8 1935.59  4786.0 1935.87
  4800.2 1934.71  4833.7 1936.33  4906.3 1935.19  4934.7 1935.58  4960.6 1934.01
  4991.4 1932.33  4998.2 1930.07  5012.2 1929.35  5012.4 1928.85  5015.9 1928.85
  5016.2 1929.35  5019.6 1931.92  5027.2 1934.71  5043.1 1934.09  5049.0 1934.64
  5060.0 1934.37  5081.8 1935.71  5089.9 1937.52  5095.3 1936.67  5103.6 1937.37
  5113.3 1937.07  5142.2 1938.17  5158.1 1937.14  5165.6 1938.59  5183.4 1938.73
#Mann=6,-1,0
  4658.7    0.07       0  4715.1   0.035       0  4833.7    0.07       0
  4960.6    0.16       0  5012.2    0.07       0  5016.2    0.16       0
Bank Sta=5012.2,5016.2
Exp/Cntr=0.3,0.1

Type RM Length L Ch R = 1,1466,81,81,81
BEGIN DESCRIPTION:
Elm 01 02 1466.48
END DESCRIPTION:
XS GIS Cut Line= 3
      1551761.21      6779846.13      1552007.71      6779997.15
      1552229.92      6780056.18
#Sta/Elev= 30
  4710.6 1937.16  4795.8 1935.98  4817.8 1935.22  4867.5 1933.38  4917.7 1933.47
  4926.1 1933.64  4933.2 1934.32  4959.5 1934.14  4969.9 1933.85  4984.8 1930.18
  4989.2 1927.56  4989.4 1927.06  4992.9 1927.06  4993.2 1927.56  4995.7 1928.58
  4999.7 1928.58  5007.2 1931.04  5017.4 1933.31  5022.6 1932.27  5027.9 1932.98
  5048.6 1932.85  5062.8 1933.33  5079.7 1934.67  5097.8 1935.32  5110.7 1936.61
  5137.9 1937.61  5172.8 1937.17  5213.1 1938.37  5218.3 1938.03  5229.6 1938.25
#Mann=5,-1,0
  4710.6   0.035       0  4817.8    0.07       0  4959.5    0.16       0
  4989.2    0.07       0  4993.2    0.16       0
Bank Sta=4989.2,4993.2
Exp/Cntr=0.3,0.1

Type RM Length L Ch R = 1,1385,145,145,145
BEGIN DESCRIPTION:
Elm 01 02 1385
END DESCRIPTION:
XS GIS Cut Line= 3
      1551728.17      6779967.63      1552004.24      6780078.75
      1552188.31      6780104.80
#Sta/Elev= 30
  4703.9 1935.88  4717.5 1935.45  4765.2 1935.42  4776.6 1934.60  4800.8 1934.08
  4849.8 1931.86  4862.2 1931.13  4873.0 1929.34  4884.1 1929.05  4894.5 1931.48
  4902.8 1932.66  4916.1 1932.11  4926.9 1932.65  4937.6 1932.46  4962.0 1932.94
  4980.7 1931.31  4986.1 1932.71  4999.2 1930.53  5004.4 1930.53  5010.4 1926.91
  5010.6 1926.41  5014.1 1926.41  5014.4 1926.91  5029.7 1929.54  5034.7 1929.67
  5042.7 1931.21  5073.0 1932.22  5113.4 1936.81  5143.7 1937.48  5187.4 1937.56
#Mann=5,-1,0
  4703.9    0.07       0  4849.8   0.035       0  4937.6    0.16       0
  5010.4    0.07       0  5014.4    0.16       0
Bank Sta=5010.4,5014.4
Exp/Cntr=0.3,0.1

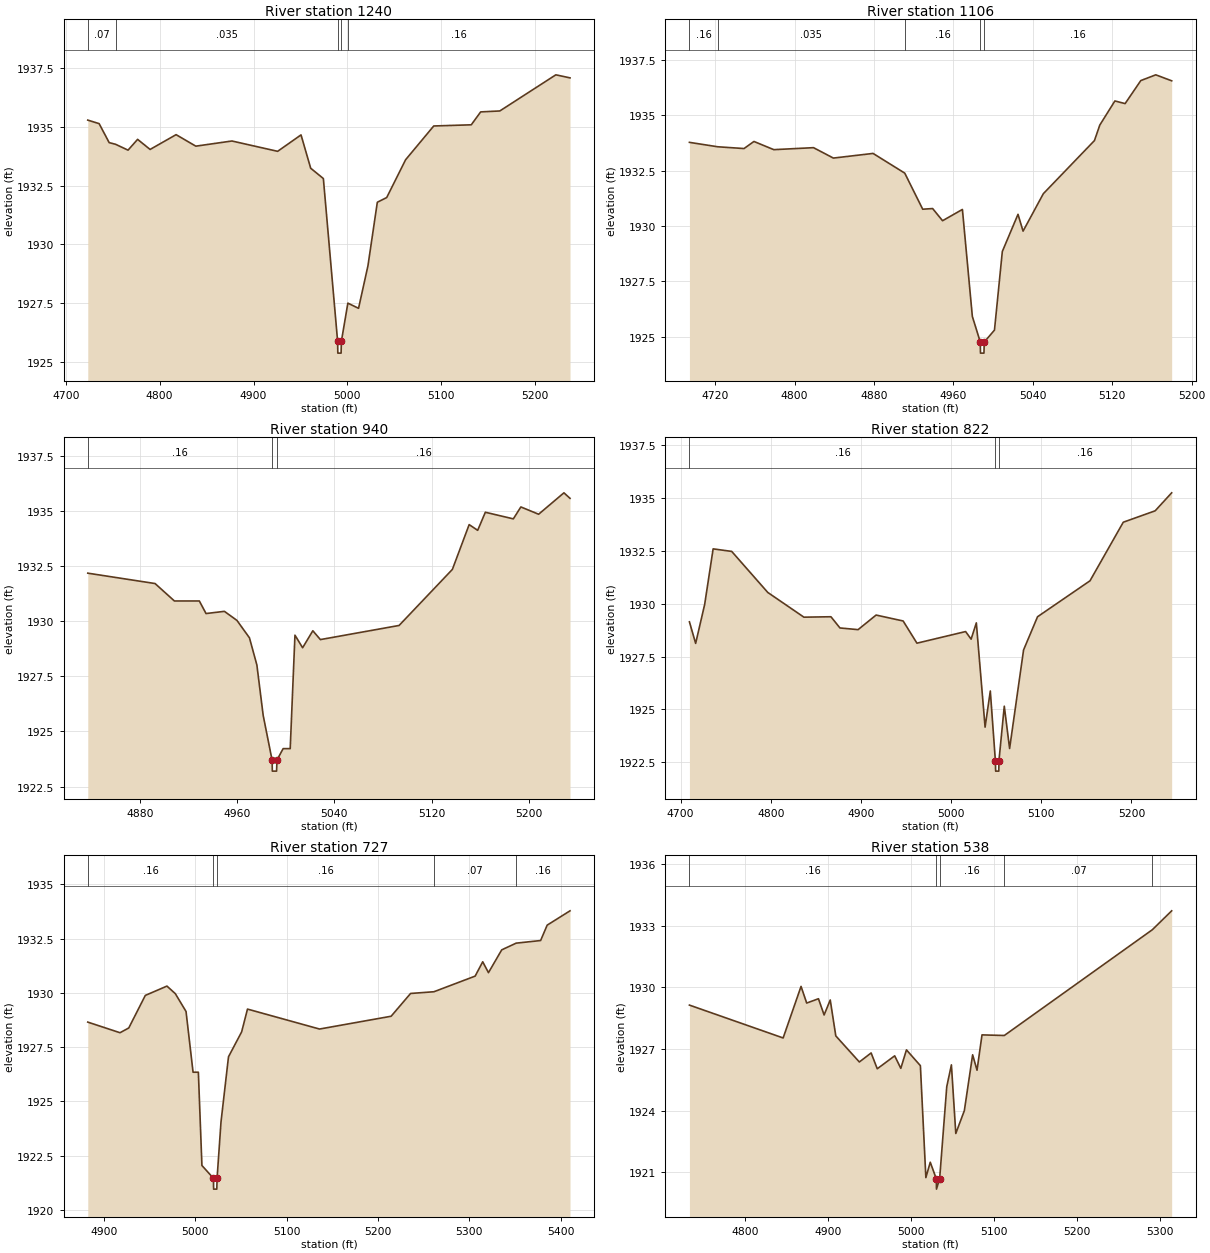
Type RM Length L Ch R = 1,1240,134,134,134
BEGIN DESCRIPTION:
Elm 01 02 1239.54
END DESCRIPTION:
XS GIS Cut Line= 3
      1551643.15      6780129.10      1551917.43      6780189.86
      1552150.07      6780179.44
#Sta/Elev= 30
  4723.4 1935.30  4735.5 1935.15  4746.2 1934.34  4753.0 1934.27  4766.3 1934.02
  4776.5 1934.48  4789.8 1934.05  4817.5 1934.68  4838.5 1934.19  4877.0 1934.41
  4925.7 1933.97  4950.6 1934.67  4960.9 1933.25  4974.4 1932.81  4989.6 1925.87
  4989.8 1925.37  4993.3 1925.37  4993.6 1925.87  5000.5 1927.50  5011.9 1927.28
  5021.9 1929.09  5031.9 1931.80  5041.9 1932.00  5062.0 1933.61  5092.0 1935.05
  5132.0 1935.10  5142.0 1935.65  5162.4 1935.69  5222.1 1937.23  5237.2 1937.10
#Mann=5,-1,0
  4723.4    0.07       0  4753.0   0.035       0  4989.6   0.035       0
  4993.6   0.035       0  5000.5    0.16       0
Bank Sta=4989.6,4993.6
Exp/Cntr=0.3,0.1

Type RM Length L Ch R = 1,1106,166,166,166
BEGIN DESCRIPTION:
Elm 01 02 1106.49
END DESCRIPTION:
XS GIS Cut Line= 3
      1551690.03      6780292.29      1551997.29      6780288.82
      1552170.48      6780245.52
#Sta/Elev= 30
  4694.0 1933.78  4722.5 1933.58  4749.0 1933.50  4759.0 1933.82  4779.0 1933.45
  4819.0 1933.54  4839.0 1933.07  4879.0 1933.28  4910.9 1932.39  4929.0 1930.76
  4939.0 1930.79  4949.0 1930.24  4969.0 1930.75  4979.0 1925.92  4987.0 1924.76
  4987.2 1924.26  4990.7 1924.26  4991.0 1924.76  5001.3 1925.30  5009.2 1928.85
  5025.0 1930.53  5030.1 1929.77  5050.5 1931.46  5102.0 1933.86  5107.4 1934.56
  5122.6 1935.65  5132.9 1935.53  5148.7 1936.57  5163.8 1936.83  5179.8 1936.56
#Mann=5,-1,0
  4694.0    0.16       0  4722.5   0.035       0  4910.9    0.16       0
  4987.0    0.07       0  4991.0    0.16       0
Bank Sta=4987,4991
Exp/Cntr=0.3,0.1

Type RM Length L Ch R = 1,940,118,118,118
BEGIN DESCRIPTION:
Elm 01 02 940.46
END DESCRIPTION:
XS GIS Cut Line= 3
      1551835.83      6780465.90      1551993.82      6780427.71
      1552181.52      6780288.22
#Sta/Elev= 30
  4837.3 1932.17  4892.6 1931.70  4908.5 1930.91  4929.0 1930.91  4934.5 1930.34
  4949.6 1930.44  4959.9 1930.03  4970.2 1929.24  4976.3 1928.01  4981.5 1925.72
  4988.8 1923.70  4989.0 1923.20  4992.5 1923.20  4992.8 1923.70  4997.9 1924.22
  5003.7 1924.22  5007.6 1929.36  5013.9 1928.79  5022.3 1929.56  5028.5 1929.16
  5093.2 1929.80  5137.0 1932.34  5150.8 1934.37  5157.8 1934.11  5164.1 1934.93
  5187.1 1934.63  5193.3 1935.17  5207.9 1934.84  5228.7 1935.81  5233.7 1935.56
#Mann=3,-1,0
  4837.3    0.16       0  4988.8    0.07       0  4992.8    0.16       0
Bank Sta=4988.8,4992.8
Exp/Cntr=0.3,0.1

Type RM Length L Ch R = 1,822,95,95,95
BEGIN DESCRIPTION:
Elm 01 02 821.75
END DESCRIPTION:
XS GIS Cut Line= 3
      1551788.14      6780524.39      1552078.68      6780511.28
      1552204.94      6780302.30
#Sta/Elev= 30
  4709.7 1929.14  4716.6 1928.12  4726.6 1929.96  4736.0 1932.59  4756.6 1932.47
  4796.6 1930.53  4836.7 1929.36  4866.7 1929.38  4876.7 1928.85  4896.8 1928.77
  4916.8 1929.46  4946.8 1929.18  4962.1 1928.13  5016.1 1928.68  5022.2 1928.32
  5028.0 1929.09  5037.7 1924.16  5043.5 1925.87  5049.1 1922.58  5049.4 1922.08
  5052.9 1922.08  5053.1 1922.58  5059.0 1925.15  5064.9 1923.15  5080.4 1927.81
  5095.9 1929.38  5154.1 1931.08  5191.0 1933.85  5226.4 1934.39  5244.7 1935.24
#Mann=3,-1,0
  4709.7    0.16       0  5049.1    0.07       0  5053.1    0.16       0
Bank Sta=5049.1,5053.1
Exp/Cntr=0.3,0.1

Type RM Length L Ch R = 1,727,189,189,189
BEGIN DESCRIPTION:
Elm 01 02 694.93
END DESCRIPTION:
XS GIS Cut Line= 3
      1551951.99      6780544.05      1552064.62      6780578.20
      1552390.53      6780827.62
#Sta/Elev= 30
  4882.3 1928.65  4917.6 1928.16  4927.2 1928.38  4945.3 1929.88  4969.0 1930.31
  4978.2 1929.96  4989.9 1929.14  4997.6 1926.34  5003.4 1926.34  5007.3 1922.04
  5019.9 1921.45  5020.1 1920.95  5023.6 1920.95  5023.9 1921.45  5028.2 1924.05
  5036.4 1927.05  5050.8 1928.20  5057.2 1929.25  5136.1 1928.33  5214.5 1928.92
  5235.8 1929.97  5261.4 1930.05  5306.5 1930.77  5314.8 1931.43  5321.1 1930.93
  5335.6 1931.98  5351.4 1932.29  5378.2 1932.41  5385.4 1933.12  5410.4 1933.78
#Mann=5,-1,0
  4882.3    0.16       0  5019.9    0.07       0  5023.9    0.16       0
  5261.4    0.07       0  5351.4    0.16       0
Bank Sta=5019.9,5023.9
Exp/Cntr=0.3,0.1

Type RM Length L Ch R = 1,538,67,67,67
BEGIN DESCRIPTION:
Elm 01 02 538.17
END DESCRIPTION:
XS GIS Cut Line= 3
      1551914.83      6780548.39      1552096.16      6780747.20
      1552390.52      6780851.86
#Sta/Elev= 30
  4732.5 1929.14  4845.5 1927.54  4867.1 1930.05  4873.9 1929.24  4888.1 1929.45
  4894.9 1928.66  4902.3 1929.39  4909.0 1927.64  4937.4 1926.37  4951.6 1926.81
  4959.0 1926.04  4980.0 1926.67  4987.4 1926.06  4994.2 1926.96  5011.0 1926.19
  5017.6 1920.74  5022.9 1921.49  5030.2 1920.68  5030.4 1920.18  5034.2 1920.68
  5042.8 1925.17  5048.4 1926.23  5053.7 1922.89  5064.0 1924.00  5074.0 1926.72
  5079.3 1925.97  5085.3 1927.69  5112.2 1927.66  5290.7 1932.81  5314.0 1933.73
#Mann=5,-1,0
  4732.5    0.16       0  5030.2    0.07       0  5034.2    0.16       0
  5112.2    0.07       0  5290.7    0.16       0
Bank Sta=5030.2,5034.2
Exp/Cntr=0.3,0.1

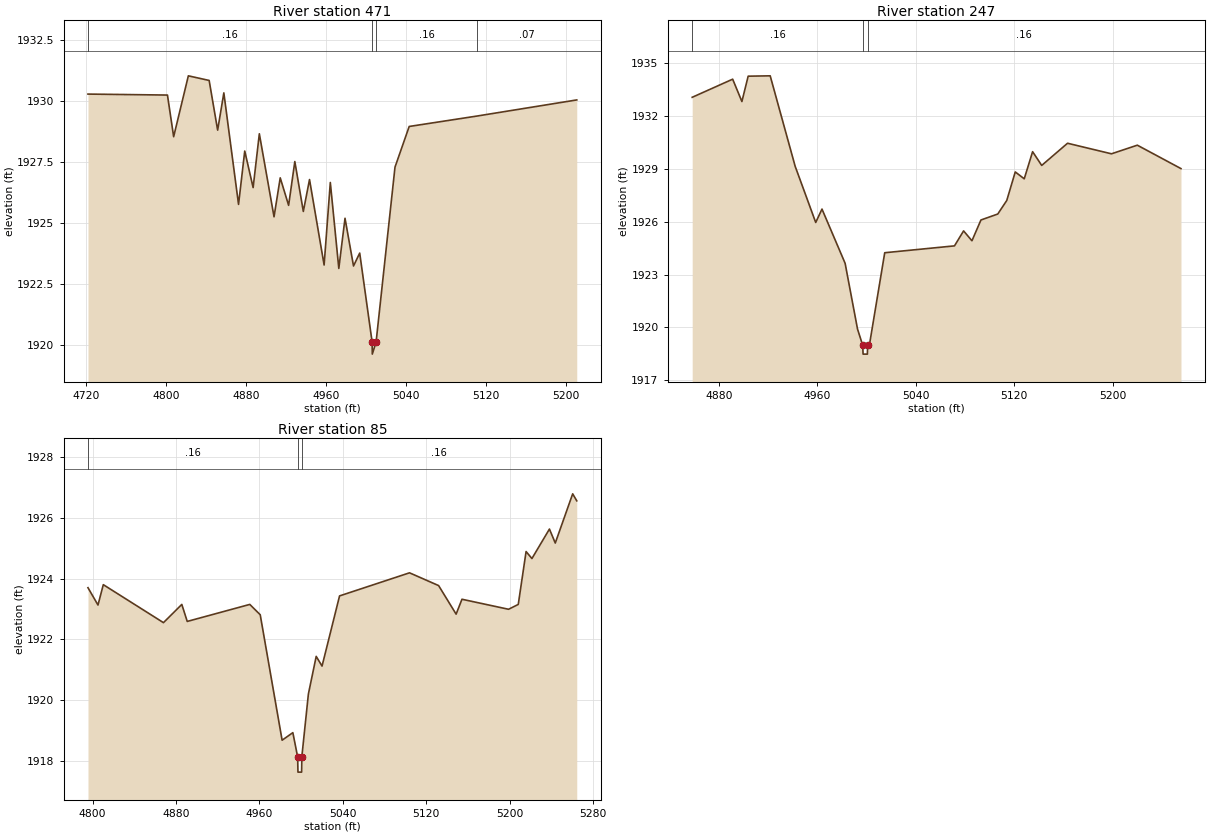
Type RM Length L Ch R = 1,471,224,224,224
BEGIN DESCRIPTION:
Elm 01 02 498.956
END DESCRIPTION:
XS GIS Cut Line= 3
      1551879.97      6780562.96      1552044.55      6780787.51
      1552198.84      6780930.71
#Sta/Elev= 30
  4721.6 1930.29  4801.1 1930.25  4807.3 1928.54  4822.0 1931.04  4842.8 1930.85
  4851.3 1928.81  4857.5 1930.34  4872.2 1925.76  4878.4 1927.95  4886.8 1926.45
  4893.0 1928.66  4907.7 1925.25  4913.9 1926.85  4922.3 1925.72  4928.5 1927.52
  4937.0 1925.47  4943.2 1926.78  4957.8 1923.27  4964.0 1926.66  4972.5 1923.13
  4978.7 1925.19  4987.2 1923.23  4993.4 1923.76  5005.8 1920.11  5006.0 1919.61
  5009.8 1920.11  5028.7 1927.29  5042.9 1928.96  5111.0 1929.39  5210.5 1930.05
#Mann=4,-1,0
  4721.6    0.16       0  5005.8    0.07       0  5009.8    0.16       0
  5111.0    0.07       0
Bank Sta=5005.8,5009.8
Exp/Cntr=0.3,0.1

Type RM Length L Ch R = 1,247,162,162,162
BEGIN DESCRIPTION:
Elm 01 02 3818
END DESCRIPTION:
XS GIS Cut Line= 3
      1551842.76      6780585.53      1551866.73      6780725.29
      1552054.57      6780898.49
#Sta/Elev= 30
  4858.2 1933.07  4891.1 1934.10  4898.6 1932.83  4903.7 1934.27  4921.6 1934.29
  4941.9 1929.15  4958.6 1925.96  4963.7 1926.72  4982.5 1923.64  4992.6 1919.90
  4996.8 1918.98  4997.1 1918.48  5000.6 1918.48  5000.8 1918.98  5002.2 1918.98
  5014.7 1924.24  5071.4 1924.63  5078.8 1925.48  5085.6 1924.92  5092.9 1926.10
  5106.6 1926.44  5113.9 1927.21  5120.8 1928.83  5128.1 1928.44  5134.9 1929.98
  5142.3 1929.20  5163.3 1930.46  5199.0 1929.86  5220.0 1930.35  5255.5 1929.02
#Mann=3,-1,0
  4858.2    0.16       0  4996.8    0.07       0  5000.8    0.16       0
Bank Sta=4996.8,5000.8
Exp/Cntr=0.3,0.1

Type RM Length L Ch R = 1,85,0,0,0
BEGIN DESCRIPTION:
Elm 01 02 3816
END DESCRIPTION:
XS GIS Cut Line= 3
      1551696.42      6780638.02      1551748.79      6780835.70
      1551985.21      6780953.86
#Sta/Elev= 30
  4795.5 1923.70  4805.1 1923.13  4810.2 1923.80  4867.9 1922.55  4885.5 1923.15
  4890.7 1922.59  4950.7 1923.15  4960.7 1922.81  4981.7 1918.68  4992.0 1918.93
  4996.6 1918.13  4996.9 1917.63  5000.4 1917.63  5000.6 1918.13  5006.9 1920.20
  5014.4 1921.44  5020.0 1921.12  5036.8 1923.43  5103.9 1924.19  5131.8 1923.77
  5148.6 1922.83  5154.2 1923.32  5198.9 1922.99  5208.2 1923.15  5215.7 1924.89
  5221.3 1924.66  5238.1 1925.63  5243.7 1925.17  5260.4 1926.79  5264.3 1926.56
#Mann=3,-1,0
  4795.5    0.16       0  4996.6    0.07       0  5000.6    0.16       0
Bank Sta=4996.6,5000.6
Exp/Cntr=0.3,0.1

Chan Stop Cuts=-1