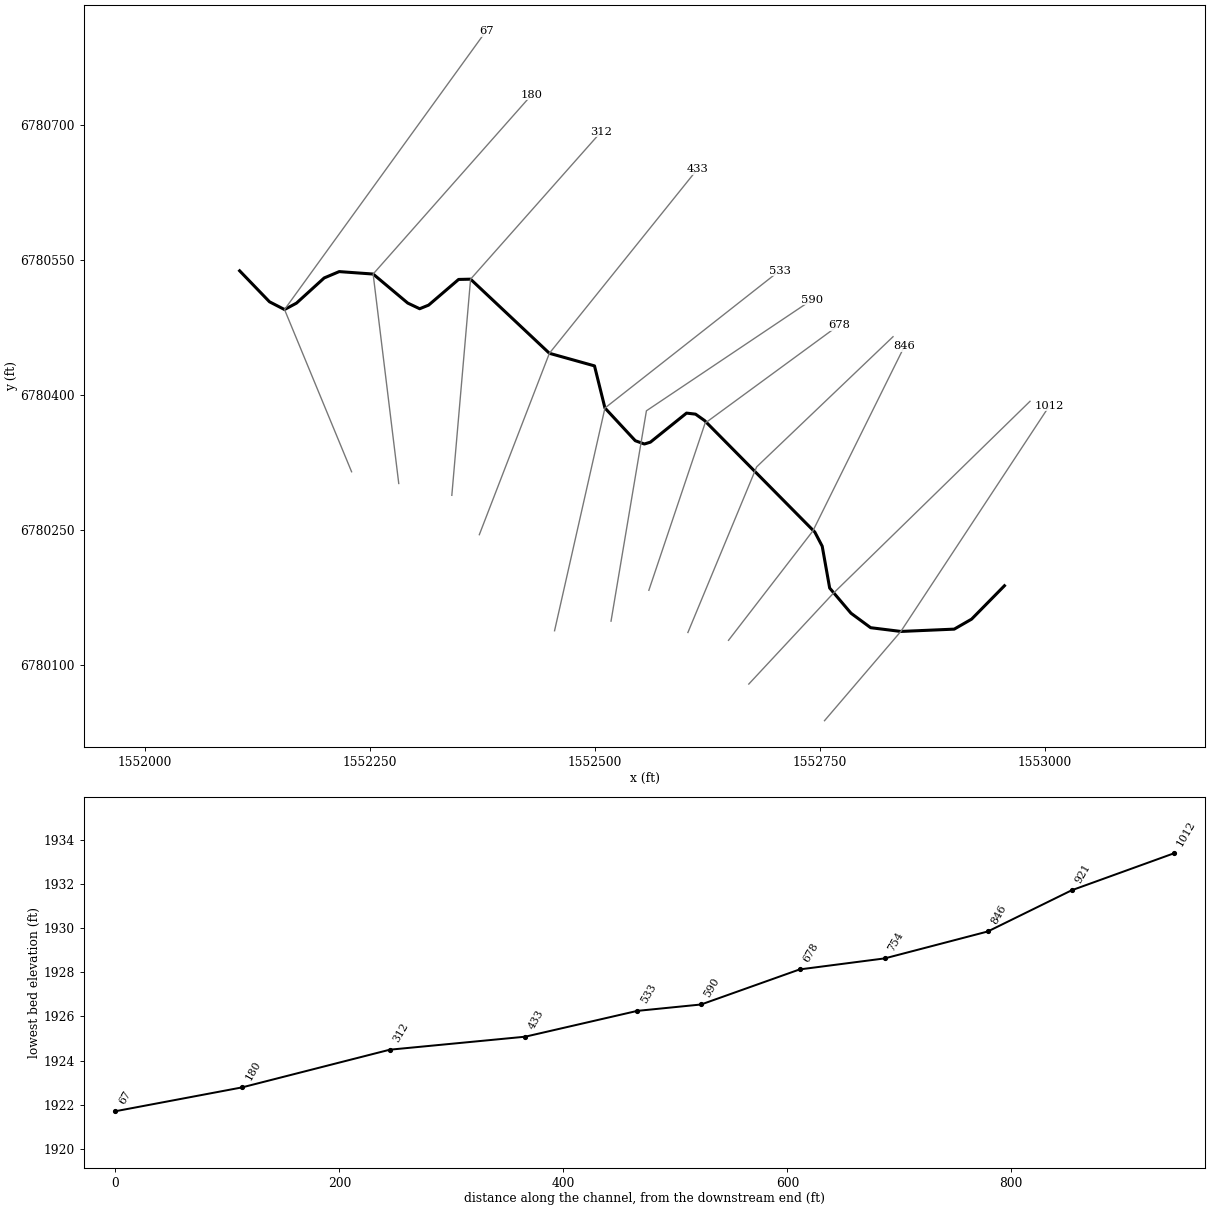
--- Elm 01 03.prj (project) ---

Proj Title=Elm 01 03 Base Level Engineering
Current Plan=p01
Default Exp/Contr=0.3,0.1
English Units
Geom File=g01
Flow File=f01
Plan File=p01
BEGIN DESCRIPTION:
Elm 01 03
END DESCRIPTION:

--- Elm 01 03.p01 (plan) ---

Plan Title=Multiple Run
Short Identifier=Multiple
Geom File=g01
Flow File=f01
Subcritical Flow
K Sum by GR= 0
Std Step Tol= 0.01
Critical Tol= 0.01
Num of Std Step Trials= 20
Max Error Tol= 0.3
Flow Tol Ratio= 0.001
Split Flow NTrial= 30
Split Flow Tol= 0.02
Split Flow Ratio= 0.02
Log Output Level= 0
Friction Slope Method= 1
Unsteady Friction Slope Method= 2
Unsteady Bridges Friction Slope Method= 1
Parabolic Critical Depth
Global Vel Dist=  1 , 1 , 1
Global Log Level= 0
CheckData=True
Encroach Param= -1, 0, 0, 0
BEGIN DESCRIPTION:
Multiple Run
END DESCRIPTION:

--- Elm 01 03.f01 (steady flow) ---

Flow Title=Multiple
Number of Profiles=7
Profile Names=10-year,25-year,50-year,1pct_min,100-year,1pct_plu,500-year
River Rch & RM= Elm 01 03,Reach-1,1012
      35      42      47      33      53      73      68
Boundary for River Rch & Prof#=Elm 01 03,Reach-1,1
Up Type=0
Dn Type=3
Dn Slope=0.005
Boundary for River Rch & Prof#=Elm 01 03,Reach-1,2
Up Type=0
Dn Type=3
Dn Slope=0.005
Boundary for River Rch & Prof#=Elm 01 03,Reach-1,3
Up Type=0
Dn Type=3
Dn Slope=0.005
Boundary for River Rch & Prof#=Elm 01 03,Reach-1,4
Up Type=0
Dn Type=3
Dn Slope=0.005
Boundary for River Rch & Prof#=Elm 01 03,Reach-1,5
Up Type=0
Dn Type=3
Dn Slope=0.005
Boundary for River Rch & Prof#=Elm 01 03,Reach-1,6
Up Type=0
Dn Type=3
Dn Slope=0.005
Boundary for River Rch & Prof#=Elm 01 03,Reach-1,7
Up Type=0
Dn Type=3
Dn Slope=0.005

--- Elm 01 03.g01 (geometry) ---

Geom Title=Existing Conditions

River Reach=Elm 01 03,Reach-1
Reach XY= 30
      1552955.00      6780188.00      1552918.48      6780150.87
      1552899.16      6780139.76      1552839.82      6780137.19
      1552806.27      6780141.36      1552784.46      6780157.42
      1552760.74      6780185.42      1552752.45      6780231.91
      1552744.21      6780247.66      1552621.66      6780371.61
      1552611.66      6780378.69      1552601.65      6780379.84
      1552561.52      6780347.57      1552554.80      6780345.50
      1552544.70      6780349.17      1552510.99      6780385.50
      1552499.38      6780432.32      1552449.25      6780446.32
      1552361.66      6780528.69      1552348.34      6780528.40
      1552315.05      6780499.87      1552305.09      6780495.84
      1552291.81      6780502.14      1552253.36      6780534.39
      1552215.64      6780537.11      1552198.93      6780530.04
      1552168.15      6780502.05      1552154.88      6780494.95
      1552138.17      6780503.56      1552105.00      6780538.00

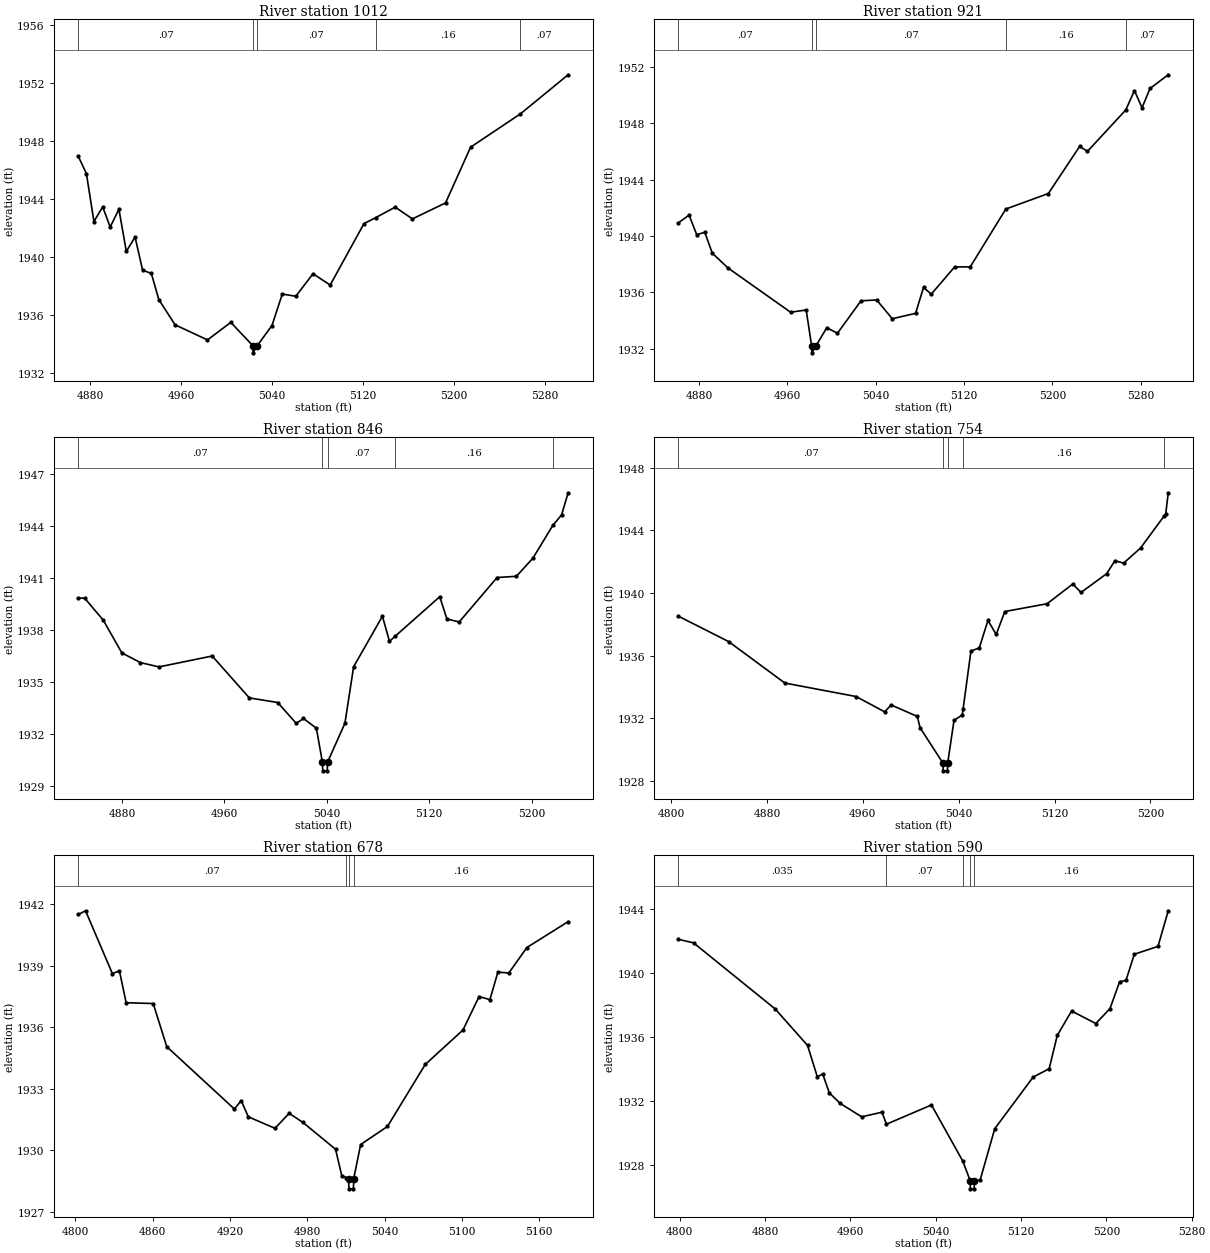
Type RM Length L Ch R = 1,1012,91,91,91
BEGIN DESCRIPTION:
Elm 01 03 1011.64
END DESCRIPTION:
XS GIS Cut Line= 3
      1552755.01      6780038.01      1552839.82      6780137.19
      1553004.99      6780387.99
#Sta/Elev= 30
  4869.5 1946.92  4876.6 1945.74  4883.2 1942.44  4890.9 1943.45  4897.5 1942.06
  4905.2 1943.28  4911.7 1940.38  4919.4 1941.37  4926.0 1939.09  4933.7 1938.86
  4940.3 1937.06  4954.6 1935.32  4983.1 1934.28  5003.6 1935.49  5022.9 1933.89
  5023.2 1933.39  5026.9 1933.89  5039.8 1935.27  5048.9 1937.44  5060.8 1937.29
  5075.9 1938.84  5091.0 1938.06  5120.7 1942.29  5130.9 1942.70  5148.2 1943.43
  5163.3 1942.62  5192.5 1943.72  5214.5 1947.56  5258.4 1949.86  5300.3 1952.55
#Mann=5,-1,0
  4869.5    0.07       0  5022.9    0.07       0  5026.9    0.07       0
  5130.9    0.16       0  5258.4    0.07       0
Bank Sta=5022.9,5026.9
Exp/Cntr=0.3,0.1

Type RM Length L Ch R = 1,921,75,75,75
BEGIN DESCRIPTION:
Elm 01 03 921.07
END DESCRIPTION:
XS GIS Cut Line= 3
      1552670.87      6780078.72      1552764.65      6780179.44
      1552983.39      6780392.97
#Sta/Elev= 30
  4861.5 1940.94  4871.1 1941.49  4878.0 1940.10  4885.3 1940.27  4892.1 1938.79
  4906.3 1937.74  4963.0 1934.60  4977.1 1934.76  4982.0 1932.22  4982.2 1931.72
  4986.0 1932.22  4995.7 1933.50  5005.4 1933.11  5026.7 1935.41  5040.9 1935.47
  5055.0 1934.14  5076.1 1934.52  5083.3 1936.36  5090.3 1935.88  5111.4 1937.81
  5125.6 1937.82  5157.8 1941.92  5196.3 1943.02  5224.6 1946.36  5231.7 1946.01
  5266.4 1948.95  5274.2 1950.32  5281.1 1949.10  5288.3 1950.47  5304.8 1951.44
#Mann=5,-1,0
  4861.5    0.07       0  4982.0    0.07       0  4986.0    0.07       0
  5157.8    0.16       0  5266.4    0.07       0
Bank Sta=4982,4986
Exp/Cntr=0.3,0.1

Type RM Length L Ch R = 1,846,92,92,92
BEGIN DESCRIPTION:
Elm 01 03 846.45
END DESCRIPTION:
XS GIS Cut Line= 3
      1552648.32      6780127.34      1552742.08      6780248.89
      1552843.89      6780454.23
#Sta/Elev= 30
  4845.8 1939.84  4850.7 1939.84  4865.3 1938.56  4879.8 1936.67  4894.3 1936.11
  4908.8 1935.86  4950.4 1936.49  4979.4 1934.07  5001.6 1933.80  5016.1 1932.59
  5021.7 1932.88  5031.8 1932.31  5036.5 1930.35  5036.8 1929.85  5040.3 1929.85
  5040.5 1930.35  5054.1 1932.60  5060.9 1935.87  5083.4 1938.79  5088.9 1937.34
  5093.6 1937.65  5128.2 1939.92  5133.8 1938.63  5143.4 1938.46  5173.0 1941.03
  5188.1 1941.10  5201.0 1942.15  5216.5 1944.04  5223.4 1944.65  5228.5 1945.93
#Mann=5,-1,0
  4845.8    0.07       0  5036.5    0.07       0  5040.5    0.07       0
  5093.6    0.16       0  5216.5    0.07       0
Bank Sta=5036.5,5040.5
Exp/Cntr=0.3,0.1

Type RM Length L Ch R = 1,754,76,76,76
BEGIN DESCRIPTION:
Elm 01 03 754.2
END DESCRIPTION:
XS GIS Cut Line= 3
      1552603.19      6780136.03      1552679.58      6780320.07
      1552831.15      6780464.75
#Sta/Elev= 30
  4806.1 1938.51  4848.0 1936.89  4894.9 1934.24  4954.3 1933.38  4978.2 1932.40
  4983.6 1932.84  5005.4 1932.11  5007.8 1931.38  5026.8 1929.13  5027.1 1928.63
  5030.6 1928.63  5030.8 1929.13  5036.1 1931.86  5043.0 1932.20  5043.7 1932.60
  5050.2 1936.28  5057.2 1936.49  5064.4 1938.24  5071.3 1937.35  5078.5 1938.81
  5113.8 1939.31  5135.2 1940.57  5142.1 1940.03  5163.5 1941.23  5170.4 1942.06
  5177.6 1941.90  5191.8 1942.87  5211.2 1944.89  5212.8 1945.06  5214.9 1946.40
#Mann=5,-1,0
  4806.1    0.07       0  5026.8    0.07       0  5030.8    0.07       0
  5043.7    0.16       0  5211.2    0.07       0
Bank Sta=5026.8,5030.8
Exp/Cntr=0.3,0.1

Type RM Length L Ch R = 1,678,88,88,88
BEGIN DESCRIPTION:
Elm 01 03 677.51
END DESCRIPTION:
XS GIS Cut Line= 3
      1552559.80      6780182.94      1552622.29      6780368.68
      1552770.83      6780477.49
#Sta/Elev= 30
  4802.4 1941.50  4808.0 1941.68  4828.8 1938.62  4834.3 1938.75  4839.5 1937.20
  4860.5 1937.16  4871.0 1935.06  4923.5 1932.02  4928.8 1932.43  4934.3 1931.64
  4955.0 1931.08  4966.0 1931.81  4976.6 1931.37  5002.0 1930.06  5006.8 1928.78
  5010.4 1928.68  5012.1 1928.63  5012.4 1928.13  5015.9 1928.13  5016.1 1928.63
  5021.5 1930.29  5042.3 1931.17  5071.6 1934.19  5100.9 1935.87  5113.4 1937.50
  5121.8 1937.35  5128.0 1938.69  5136.5 1938.65  5150.5 1939.89  5182.5 1941.15
#Mann=4,-1,0
  4802.4    0.07       0  5010.4    0.16       0  5012.1    0.07       0
  5016.1    0.16       0
Bank Sta=5012.1,5016.1
Exp/Cntr=0.3,0.1

Type RM Length L Ch R = 1,590,57,57,57
BEGIN DESCRIPTION:
Elm 01 03 589.95
END DESCRIPTION:
XS GIS Cut Line= 3
      1552517.75      6780148.63      1552557.08      6780382.40
      1552741.41      6780506.01
#Sta/Elev= 30
  4799.0 1942.10  4813.1 1941.88  4889.6 1937.76  4920.0 1935.48  4929.1 1933.53
  4934.2 1933.70  4940.3 1932.53  4950.5 1931.87  4970.7 1931.03  4989.7 1931.32
  4993.9 1930.57  5036.1 1931.77  5065.6 1928.25  5072.4 1927.04  5072.6 1926.54
  5076.1 1926.54  5076.4 1927.04  5081.7 1927.09  5095.4 1930.29  5131.4 1933.51
  5146.4 1934.03  5154.0 1936.11  5167.4 1937.63  5190.1 1936.85  5203.4 1937.78
  5212.4 1939.45  5218.4 1939.54  5226.2 1941.17  5248.4 1941.66  5258.0 1943.88
#Mann=5,-1,0
  4799.0   0.035       0  4993.9    0.07       0  5065.6    0.16       0
  5072.4    0.07       0  5076.4    0.16       0
Bank Sta=5072.4,5076.4
Exp/Cntr=0.3,0.1

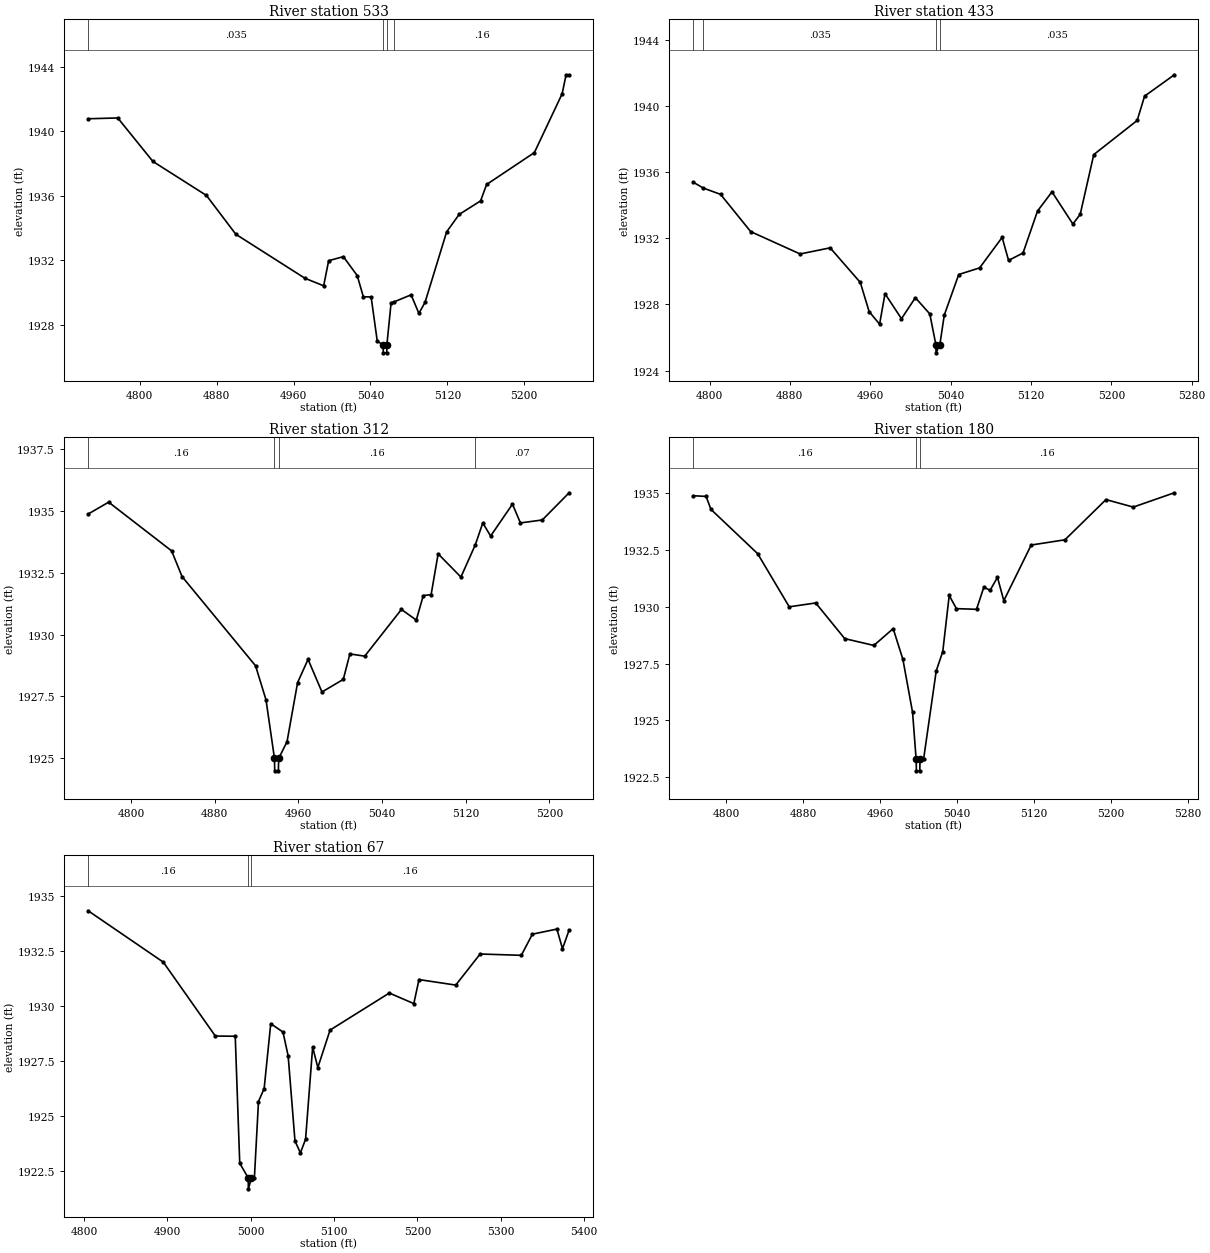
Type RM Length L Ch R = 1,533,100,100,100
BEGIN DESCRIPTION:
Elm 01 03 533.373
END DESCRIPTION:
XS GIS Cut Line= 3
      1552454.99      6780137.96      1552510.99      6780385.50
      1552705.02      6780538.02
#Sta/Elev= 30
  4746.2 1940.78  4777.0 1940.83  4813.6 1938.13  4869.3 1936.02  4899.9 1933.61
  4971.8 1930.88  4991.3 1930.41  4996.5 1931.97  5011.8 1932.22  5026.2 1931.05
  5032.6 1929.73  5040.7 1929.72  5047.1 1926.97  5053.1 1926.75  5053.4 1926.25
  5056.9 1926.25  5057.1 1926.75  5061.5 1929.36  5064.8 1929.42  5082.3 1929.85
  5090.4 1928.70  5096.8 1929.38  5119.3 1933.76  5132.3 1934.84  5154.6 1935.68
  5160.9 1936.70  5210.6 1938.68  5239.5 1942.33  5243.6 1943.51  5246.8 1943.51
#Mann=4,-1,0
  4746.2   0.035       0  5053.1   0.035       0  5057.1   0.035       0
  5064.8    0.16       0
Bank Sta=5053.1,5057.1
Exp/Cntr=0.3,0.1

Type RM Length L Ch R = 1,433,121,121,121
BEGIN DESCRIPTION:
Elm 01 03 3832
END DESCRIPTION:
XS GIS Cut Line= 3
      1552371.38      6780244.73      1552449.25      6780446.32
      1552613.85      6780651.06
#Sta/Elev= 30
  4783.9 1935.38  4793.8 1935.03  4811.0 1934.65  4841.0 1932.40  4890.2 1931.05
  4920.1 1931.42  4950.1 1929.33  4958.9 1927.57  4969.3 1926.81  4974.7 1928.65
  4991.1 1927.14  5004.9 1928.41  5019.3 1927.43  5025.3 1925.58  5025.5 1925.08
  5029.3 1925.58  5033.7 1927.36  5048.1 1929.81  5068.9 1930.21  5091.3 1932.05
  5097.7 1930.66  5112.1 1931.11  5126.5 1933.64  5140.9 1934.80  5161.7 1932.86
  5169.0 1933.44  5182.5 1937.05  5225.7 1939.11  5233.1 1940.58  5262.7 1941.87
#Mann=4,-1,0
  4783.9    0.16       0  4793.8   0.035       0  5025.3   0.035       0
  5029.3   0.035       0
Bank Sta=5025.3,5029.3
Exp/Cntr=0.3,0.1

Type RM Length L Ch R = 1,312,132,132,132
BEGIN DESCRIPTION:
Elm 01 03 3830
END DESCRIPTION:
XS GIS Cut Line= 3
      1552340.82      6780288.49      1552361.66      6780528.69
      1552506.80      6780692.55
#Sta/Elev= 30
  4758.9 1934.88  4778.5 1935.36  4838.7 1933.39  4848.7 1932.35  4919.0 1928.74
  4929.0 1927.36  4937.1 1924.99  4937.3 1924.49  4940.8 1924.49  4941.1 1924.99
  4949.1 1925.67  4959.2 1928.06  4969.2 1929.00  4982.5 1927.68  5002.9 1928.19
  5009.2 1929.22  5023.4 1929.13  5058.5 1931.02  5072.7 1930.59  5079.4 1931.58
  5086.9 1931.62  5093.6 1933.27  5115.4 1932.33  5129.2 1933.64  5136.3 1934.52
  5143.8 1933.99  5164.7 1935.28  5172.3 1934.52  5193.2 1934.64  5218.9 1935.74
#Mann=4,-1,0
  4758.9    0.16       0  4937.1    0.07       0  4941.1    0.16       0
  5129.2    0.07       0
Bank Sta=4937.1,4941.1
Exp/Cntr=0.3,0.1

Type RM Length L Ch R = 1,180,113,113,113
BEGIN DESCRIPTION:
Elm 01 03 3828
END DESCRIPTION:
XS GIS Cut Line= 3
      1552281.83      6780301.62      1552253.36      6780534.39
      1552429.52      6780733.56
#Sta/Elev= 30
  4765.5 1934.89  4778.8 1934.86  4783.8 1934.29  4832.4 1932.34  4865.3 1930.00
  4892.8 1930.17  4923.0 1928.60  4953.3 1928.30  4973.4 1929.04  4983.5 1927.69
  4993.6 1925.35  4997.3 1923.28  4997.6 1922.78  5001.1 1922.78  5001.3 1923.28
  5005.0 1923.28  5018.2 1927.18  5025.0 1928.03  5031.7 1930.50  5039.2 1929.92
  5060.1 1929.89  5067.7 1930.86  5074.3 1930.73  5081.9 1931.30  5088.5 1930.27
  5117.0 1932.72  5152.1 1932.95  5194.8 1934.72  5223.2 1934.39  5265.9 1935.02
#Mann=3,-1,0
  4765.5    0.16       0  4997.3    0.07       0  5001.3    0.16       0
Bank Sta=4997.3,5001.3
Exp/Cntr=0.3,0.1

Type RM Length L Ch R = 1,67,0,0,0
BEGIN DESCRIPTION:
Elm 01 03 3824
END DESCRIPTION:
XS GIS Cut Line= 3
      1552229.42      6780314.65      1552154.88      6780494.95
      1552378.91      6780804.48
#Sta/Elev= 30
  4804.9 1934.31  4895.1 1931.98  4957.5 1928.63  4981.4 1928.62  4986.8 1922.86
  4996.9 1922.20  4997.2 1921.70  5000.9 1922.20  5004.4 1922.20  5009.3 1925.66
  5016.1 1926.25  5024.0 1929.19  5038.7 1928.81  5044.9 1927.73  5053.1 1923.87
  5059.6 1923.33  5065.8 1923.95  5074.3 1928.13  5080.5 1927.20  5095.2 1928.90
  5166.3 1930.58  5195.7 1930.10  5201.9 1931.19  5246.0 1930.94  5275.3 1932.35
  5324.7 1932.29  5338.0 1933.25  5367.4 1933.48  5374.1 1932.59  5382.1 1933.44
#Mann=3,-1,0
  4804.9    0.16       0  4996.9    0.07       0  5000.9    0.16       0
Bank Sta=4996.9,5000.9
Exp/Cntr=0.3,0.1

Chan Stop Cuts=-1