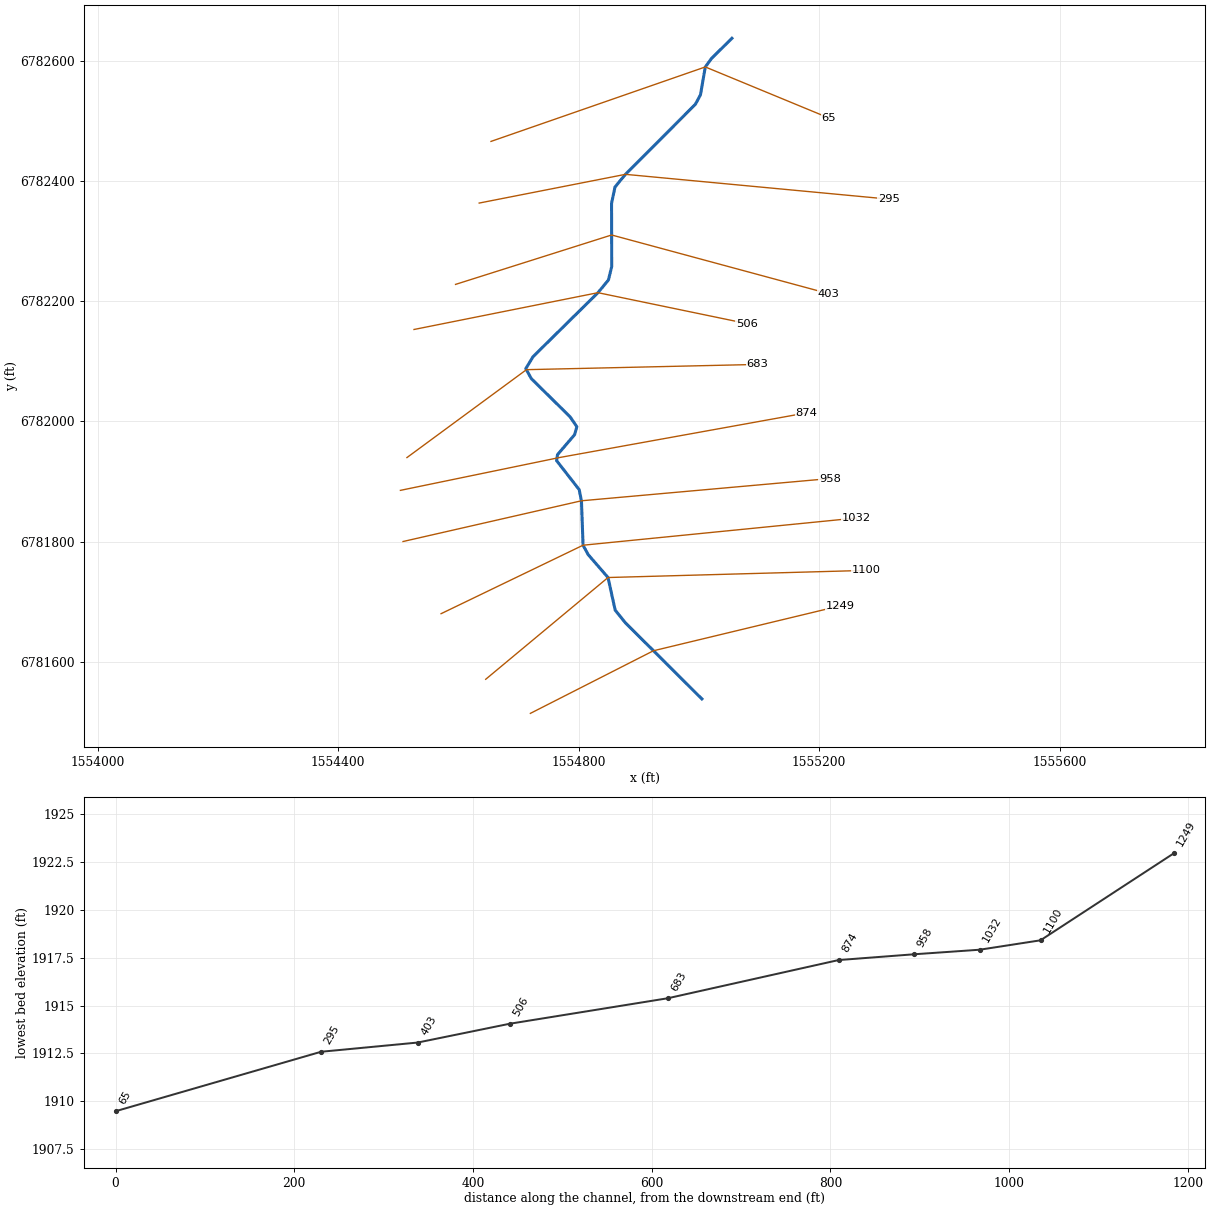
--- Elm 01 04.prj (project) ---

Proj Title=Elm 01 04 Base Level Engineering
Current Plan=p01
Default Exp/Contr=0.3,0.1
English Units
Geom File=g01
Flow File=f01
Plan File=p01
BEGIN DESCRIPTION:
Elm 01 04
END DESCRIPTION:

--- Elm 01 04.p01 (plan) ---

Plan Title=Multiple Run
Short Identifier=Multiple
Geom File=g01
Flow File=f01
Subcritical Flow
K Sum by GR= 0
Std Step Tol= 0.01
Critical Tol= 0.01
Num of Std Step Trials= 20
Max Error Tol= 0.3
Flow Tol Ratio= 0.001
Split Flow NTrial= 30
Split Flow Tol= 0.02
Split Flow Ratio= 0.02
Log Output Level= 0
Friction Slope Method= 1
Unsteady Friction Slope Method= 2
Unsteady Bridges Friction Slope Method= 1
Parabolic Critical Depth
Global Vel Dist=  1 , 1 , 1
Global Log Level= 0
CheckData=True
Encroach Param= -1, 0, 0, 0
BEGIN DESCRIPTION:
Multiple Run
END DESCRIPTION:

--- Elm 01 04.f01 (steady flow) ---

Flow Title=Multiple
Number of Profiles=7
Profile Names=10-year,25-year,50-year,1pct_min,100-year,1pct_plu,500-year
River Rch & RM= Elm 01 04,Reach-1,1249
      60      76      88      64     102     140     137
Boundary for River Rch & Prof#=Elm 01 04,Reach-1,1
Up Type=0
Dn Type=3
Dn Slope=0.005
Boundary for River Rch & Prof#=Elm 01 04,Reach-1,2
Up Type=0
Dn Type=3
Dn Slope=0.005
Boundary for River Rch & Prof#=Elm 01 04,Reach-1,3
Up Type=0
Dn Type=3
Dn Slope=0.005
Boundary for River Rch & Prof#=Elm 01 04,Reach-1,4
Up Type=0
Dn Type=3
Dn Slope=0.005
Boundary for River Rch & Prof#=Elm 01 04,Reach-1,5
Up Type=0
Dn Type=3
Dn Slope=0.005
Boundary for River Rch & Prof#=Elm 01 04,Reach-1,6
Up Type=0
Dn Type=3
Dn Slope=0.005
Boundary for River Rch & Prof#=Elm 01 04,Reach-1,7
Up Type=0
Dn Type=3
Dn Slope=0.005

--- Elm 01 04.g01 (geometry) ---

Geom Title=Existing Conditions

River Reach=Elm 01 04,Reach-1
Reach XY= 30
      1555005.00      6781538.00      1554941.50      6781601.26
      1554878.00      6781664.53      1554860.83      6781685.70
      1554848.86      6781740.17      1554815.83      6781778.35
      1554807.33      6781793.97      1554804.65      6781867.95
      1554800.92      6781886.50      1554763.28      6781934.78
      1554764.79      6781944.74      1554793.30      6781978.01
      1554796.98      6781991.34      1554785.54      6782008.00
      1554721.26      6782071.33      1554712.10      6782088.00
      1554724.22      6782108.00      1554778.18      6782161.23
      1554832.14      6782214.47      1554849.53      6782235.55
      1554855.02      6782257.99      1554854.88      6782310.55
      1554854.73      6782363.11      1554860.47      6782390.45
      1554877.86      6782411.53      1554994.30      6782528.29
      1555002.66      6782543.97      1555010.71      6782590.35
      1555021.42      6782604.92      1555055.00      6782638.00

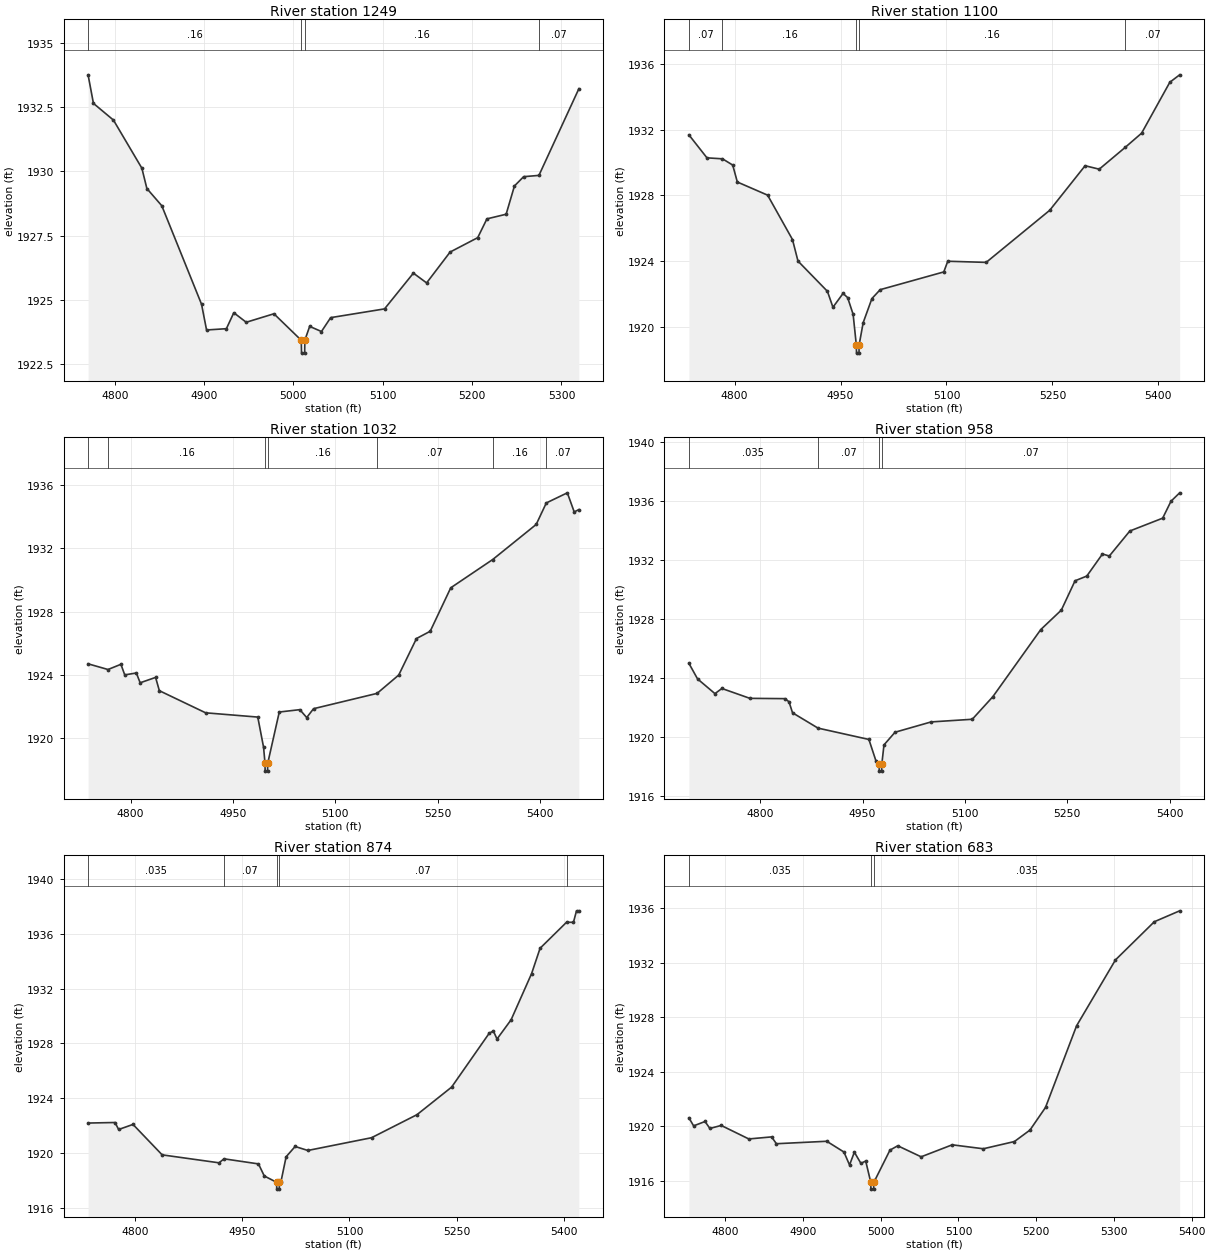
Type RM Length L Ch R = 1,1249,149,149,149
BEGIN DESCRIPTION:
Elm 01 04 3814
END DESCRIPTION:
XS GIS Cut Line= 3
      1554719.69      6781513.95      1554924.47      6781618.23
      1555235.09      6781693.04
#Sta/Elev= 30
  4770.2 1933.75  4776.2 1932.64  4798.6 1931.99  4830.4 1930.12  4836.0 1929.33
  4852.7 1928.66  4897.2 1924.83  4902.8 1923.83  4925.0 1923.88  4933.3 1924.50
  4947.2 1924.13  4978.2 1924.46  5008.8 1923.43  5009.1 1922.93  5012.6 1922.93
  5012.8 1923.43  5018.2 1923.97  5031.4 1923.77  5041.7 1924.31  5102.0 1924.65
  5134.3 1926.04  5149.1 1925.66  5175.4 1926.86  5206.3 1927.42  5216.6 1928.15
  5238.1 1928.33  5247.4 1929.43  5257.7 1929.79  5274.8 1929.84  5319.5 1933.21
#Mann=4,-1,0
  4770.2    0.16       0  5008.8    0.07       0  5012.8    0.16       0
  5274.8    0.07       0
Bank Sta=5008.8,5012.8
Exp/Cntr=0.3,0.1

Type RM Length L Ch R = 1,1100,68,68,68
BEGIN DESCRIPTION:
Elm 01 04 3812
END DESCRIPTION:
XS GIS Cut Line= 3
      1554645.38      6781570.72      1554848.86      6781740.17
      1555278.90      6781752.05
#Sta/Elev= 30
  4735.2 1931.68  4760.8 1930.28  4782.8 1930.22  4797.3 1929.84  4803.8 1928.81
  4846.7 1928.01  4881.9 1925.31  4889.7 1924.00  4931.4 1922.16  4939.2 1921.19
  4953.5 1922.03  4960.0 1921.78  4967.8 1920.76  4972.3 1918.90  4972.6 1918.40
  4976.1 1918.40  4976.3 1918.90  4982.0 1920.25  4994.4 1921.72  5006.1 1922.26
  5096.2 1923.34  5101.8 1923.99  5156.2 1923.92  5246.2 1927.09  5296.3 1929.80
  5316.3 1929.59  5352.9 1930.91  5376.3 1931.78  5416.3 1934.88  5430.2 1935.33
#Mann=5,-1,0
  4735.2    0.07       0  4782.8    0.16       0  4972.3    0.07       0
  4976.3    0.16       0  5352.9    0.07       0
Bank Sta=4972.3,4976.3
Exp/Cntr=0.3,0.1

Type RM Length L Ch R = 1,1032,74,74,74
BEGIN DESCRIPTION:
Elm 01 04 3810
END DESCRIPTION:
XS GIS Cut Line= 3
      1554571.11      6781679.94      1554807.33      6781793.97
      1555261.78      6781839.24
#Sta/Elev= 30
  4737.7 1924.70  4766.9 1924.34  4785.8 1924.67  4791.4 1924.00  4808.4 1924.12
  4814.0 1923.50  4836.6 1923.84  4842.1 1923.00  4909.9 1921.60  4986.3 1921.33
  4994.8 1919.42  4996.9 1918.41  4997.1 1917.91  5000.6 1917.91  5000.9 1918.41
  5017.8 1921.65  5047.9 1921.80  5058.0 1921.30  5068.0 1921.86  5161.1 1922.83
  5192.8 1923.99  5218.8 1926.30  5238.9 1926.76  5269.0 1929.51  5330.5 1931.30
  5394.2 1933.52  5409.0 1934.88  5439.8 1935.52  5449.9 1934.31  5456.7 1934.46
#Mann=7,-1,0
  4737.7    0.07       0  4766.9    0.16       0  4996.9    0.07       0
  5000.9    0.16       0  5161.1    0.07       0  5330.5    0.16       0
  5409.0    0.07       0
Bank Sta=4996.9,5000.9
Exp/Cntr=0.3,0.1

Type RM Length L Ch R = 1,958,84,84,84
BEGIN DESCRIPTION:
Elm 01 04 958.091
END DESCRIPTION:
XS GIS Cut Line= 3
      1554507.81      6781800.11      1554804.65      6781867.95
      1555217.70      6781904.95
#Sta/Elev= 30
  4695.5 1924.99  4708.2 1923.93  4733.7 1922.93  4743.9 1923.28  4784.9 1922.61
  4836.2 1922.59  4842.2 1922.38  4847.4 1921.63  4884.7 1920.59  4959.3 1919.82
  4969.6 1918.37  4974.3 1918.17  4974.5 1917.67  4978.0 1917.67  4978.3 1918.17
  4981.4 1919.45  4997.6 1920.31  5050.5 1921.01  5110.8 1921.19  5140.9 1922.72
  5211.2 1927.28  5241.3 1928.60  5261.4 1930.59  5278.6 1930.91  5301.6 1932.41
  5311.6 1932.27  5341.7 1933.97  5389.8 1934.84  5402.0 1935.99  5414.7 1936.56
#Mann=4,-1,0
  4695.5   0.035       0  4884.7    0.07       0  4974.3    0.07       0
  4978.3    0.07       0
Bank Sta=4974.3,4978.3
Exp/Cntr=0.3,0.1

Type RM Length L Ch R = 1,874,191,191,191
BEGIN DESCRIPTION:
Elm 01 04 873.56
END DESCRIPTION:
XS GIS Cut Line= 3
      1554503.44      6781885.30      1554767.74      6781939.91
      1555178.40      6782014.18
#Sta/Elev= 30
  4734.0 1922.19  4771.7 1922.23  4776.8 1921.72  4796.9 1922.09  4837.7 1919.87
  4917.3 1919.29  4924.4 1919.58  4972.6 1919.21  4980.7 1918.33  4997.9 1917.87
  4998.2 1917.37  5001.7 1917.37  5001.9 1917.87  5003.9 1917.87  5011.3 1919.73
  5023.9 1920.48  5041.7 1920.19  5130.9 1921.12  5194.5 1922.80  5243.0 1924.81
  5295.8 1928.75  5301.5 1928.90  5306.6 1928.32  5326.3 1929.72  5355.0 1933.09
  5366.9 1934.94  5404.0 1936.84  5413.6 1936.83  5417.9 1937.67  5421.2 1937.67
#Mann=5,-1,0
  4734.0   0.035       0  4924.4    0.07       0  4997.9    0.07       0
  5001.9    0.07       0  5404.0   0.035       0
Bank Sta=4997.9,5001.9
Exp/Cntr=0.3,0.1

Type RM Length L Ch R = 1,683,177,177,177
BEGIN DESCRIPTION:
Elm 01 04 682.79
END DESCRIPTION:
XS GIS Cut Line= 3
      1554514.33      6781939.90      1554713.13      6782086.27
      1555097.56      6782095.00
#Sta/Elev= 30
  4753.2 1920.61  4759.3 1920.02  4774.0 1920.34  4780.2 1919.83  4794.8 1920.05
  4830.3 1919.06  4859.6 1919.21  4865.8 1918.71  4930.6 1918.89  4952.7 1918.10
  4959.9 1917.15  4966.1 1918.09  4974.5 1917.27  4980.7 1917.44  4987.2 1915.88
  4987.4 1915.38  4990.9 1915.38  4991.2 1915.88  5011.9 1918.24  5021.9 1918.56
  5052.0 1917.75  5092.0 1918.63  5132.0 1918.34  5172.0 1918.87  5192.0 1919.71
  5212.0 1921.37  5252.0 1927.36  5302.0 1932.19  5352.0 1934.99  5384.6 1935.79
#Mann=3,-1,0
  4753.2   0.035       0  4987.2   0.035       0  4991.2   0.035       0
Bank Sta=4987.2,4991.2
Exp/Cntr=0.3,0.1

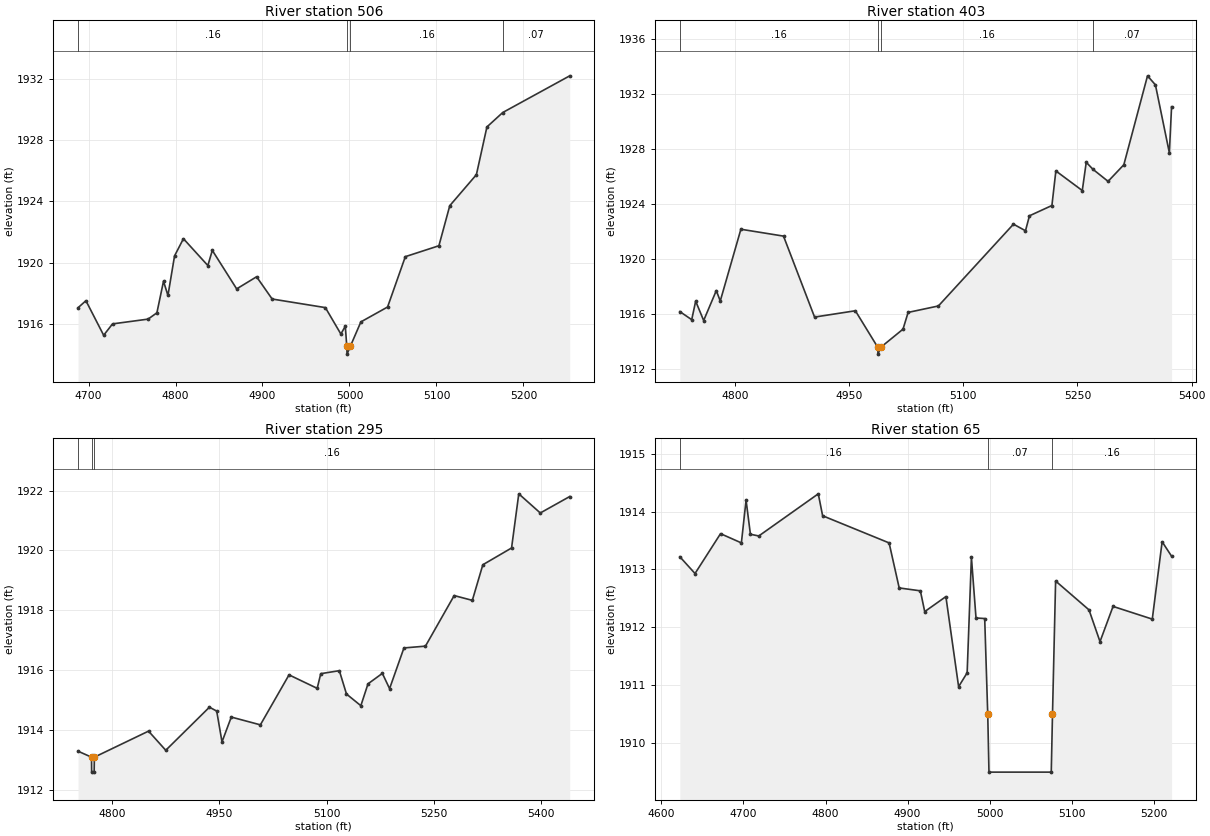
Type RM Length L Ch R = 1,506,103,103,103
BEGIN DESCRIPTION:
Elm 01 04 505.78
END DESCRIPTION:
XS GIS Cut Line= 3
      1554526.11      6782153.19      1554832.14      6782214.47
      1555080.05      6782162.99
#Sta/Elev= 30
  4687.9 1917.07  4697.0 1917.53  4717.4 1915.28  4727.6 1916.02  4768.4 1916.33
  4778.6 1916.74  4786.2 1918.80  4791.3 1917.87  4798.9 1920.45  4809.1 1921.57
  4837.2 1919.82  4842.3 1920.81  4870.3 1918.30  4893.2 1919.09  4911.1 1917.64
  4972.3 1917.08  4990.1 1915.36  4995.2 1915.87  4996.9 1914.55  4997.2 1914.05
  5000.9 1914.55  5013.1 1916.15  5043.8 1917.12  5064.2 1920.40  5102.8 1921.11
  5115.3 1923.72  5145.9 1925.74  5158.0 1928.85  5176.2 1929.79  5253.2 1932.18
#Mann=4,-1,0
  4687.9    0.16       0  4996.9    0.07       0  5000.9    0.16       0
  5176.2    0.07       0
Bank Sta=4996.9,5000.9
Exp/Cntr=0.3,0.1

Type RM Length L Ch R = 1,403,108,108,108
BEGIN DESCRIPTION:
Elm 01 04 3808
END DESCRIPTION:
XS GIS Cut Line= 3
      1554595.20      6782228.27      1554854.88      6782310.55
      1555215.51      6782212.97
#Sta/Elev= 30
  4727.6 1916.17  4743.2 1915.58  4748.4 1916.93  4758.9 1915.52  4775.5 1917.70
  4780.7 1916.94  4807.8 1922.17  4863.8 1921.67  4904.6 1915.77  4958.2 1916.23
  4987.6 1913.57  4987.9 1913.07  4991.6 1913.57  5020.8 1914.89  5027.5 1916.11
  5067.3 1916.58  5165.9 1922.54  5181.7 1922.06  5186.9 1923.15  5216.4 1923.90
  5221.6 1926.42  5256.3 1924.99  5261.5 1927.05  5270.3 1926.54  5290.2 1925.66
  5310.9 1926.87  5342.0 1933.35  5352.4 1932.69  5370.7 1927.74  5373.6 1931.10
#Mann=4,-1,0
  4727.6    0.16       0  4987.6    0.07       0  4991.6    0.16       0
  5270.3    0.07       0
Bank Sta=4987.6,4991.6
Exp/Cntr=0.3,0.1

Type RM Length L Ch R = 1,295,230,230,230
BEGIN DESCRIPTION:
Elm 01 04 3806
END DESCRIPTION:
XS GIS Cut Line= 3
      1554634.52      6782363.70      1554877.86      6782411.53
      1555316.02      6782370.24
#Sta/Elev= 30
  4752.0 1913.29  4770.9 1913.09  4771.1 1912.59  4774.6 1912.59  4774.9 1913.09
  4850.7 1913.96  4874.8 1913.32  4935.9 1914.76  4946.1 1914.63  4953.5 1913.60
  4966.5 1914.43  5007.2 1914.17  5047.3 1915.84  5086.7 1915.39  5091.7 1915.88
  5117.7 1915.98  5127.7 1915.20  5147.8 1914.81  5157.8 1915.54  5177.9 1915.89
  5188.0 1915.38  5208.1 1916.74  5238.2 1916.80  5278.4 1918.49  5303.8 1918.33
  5318.5 1919.52  5358.7 1920.08  5368.8 1921.89  5398.9 1921.25  5440.1 1921.80
#Mann=3,-1,0
  4752.0    0.16       0  4770.9    0.07       0  4774.9    0.16       0
Bank Sta=4770.9,4774.9
Exp/Cntr=0.3,0.1

Type RM Length L Ch R = 1,65,0,0,0
BEGIN DESCRIPTION:
Elm 01 04 3804
END DESCRIPTION:
XS GIS Cut Line= 3
      1554654.15      6782466.36      1555010.71      6782590.35
      1555215.59      6782505.66
#Sta/Elev= 30
  4622.5 1913.22  4641.0 1912.93  4672.1 1913.62  4697.5 1913.46  4703.2 1914.20
  4708.5 1913.61  4718.7 1913.58  4791.2 1914.31  4796.5 1913.93  4877.5 1913.46
  4889.8 1912.68  4915.6 1912.63  4920.9 1912.27  4946.7 1912.53  4962.2 1910.97
  4972.6 1911.21  4977.8 1913.21  4983.4 1912.16  4994.0 1912.15  4997.7 1910.49
  4999.2 1909.49  5075.1 1909.49  5076.6 1910.49  5080.4 1912.80  5121.1 1912.30
  5134.5 1911.75  5150.4 1912.36  5198.2 1912.14  5210.2 1913.48  5221.7 1913.23
#Mann=3,-1,0
  4622.5    0.16       0  4997.7    0.07       0  5076.6    0.16       0
Bank Sta=4997.7,5076.6
Exp/Cntr=0.3,0.1

Chan Stop Cuts=-1