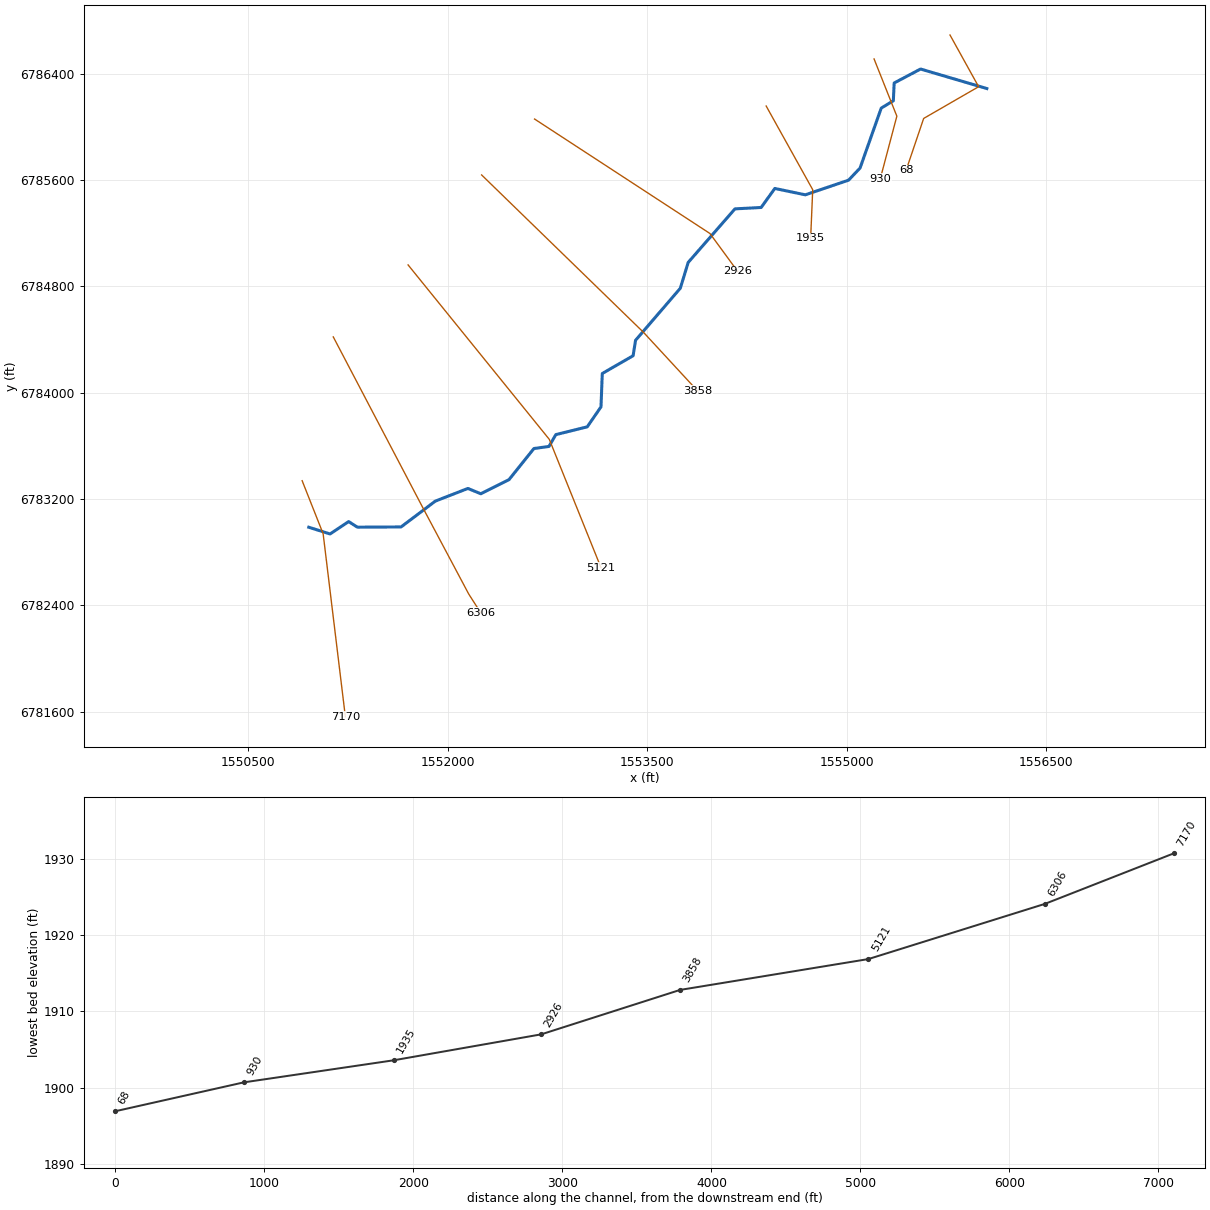
--- Elm 01 05.prj (project) ---

Proj Title=Elm 01 05 Base Level Engineering
Current Plan=p01
Default Exp/Contr=0.3,0.1
English Units
Geom File=g01
Flow File=f01
Plan File=p01
BEGIN DESCRIPTION:
Elm 01 05
END DESCRIPTION:

--- Elm 01 05.p01 (plan) ---

Plan Title=Multiple Run
Short Identifier=Multiple
Geom File=g01
Flow File=f01
Subcritical Flow
K Sum by GR= 0
Std Step Tol= 0.01
Critical Tol= 0.01
Num of Std Step Trials= 20
Max Error Tol= 0.3
Flow Tol Ratio= 0.001
Split Flow NTrial= 30
Split Flow Tol= 0.02
Split Flow Ratio= 0.02
Log Output Level= 0
Friction Slope Method= 1
Unsteady Friction Slope Method= 2
Unsteady Bridges Friction Slope Method= 1
Parabolic Critical Depth
Global Vel Dist=  1 , 1 , 1
Global Log Level= 0
CheckData=True
Encroach Param= -1, 0, 0, 0
BEGIN DESCRIPTION:
Multiple Run
END DESCRIPTION:

--- Elm 01 05.f01 (steady flow) ---

Flow Title=Multiple
Number of Profiles=7
Profile Names=10-year,25-year,50-year,1pct_min,100-year,1pct_plu,500-year
River Rch & RM= Elm 01 05,Reach-1,7170
     256     361     449     348     557     767     867
River Rch & RM= Elm 01 05,Reach-1,6306
     397     573     726     571     915    1260    1470
River Rch & RM= Elm 01 05,Reach-1,5121
     425     608     765     596     955    1310    1510
Boundary for River Rch & Prof#=Elm 01 05,Reach-1,1
Up Type=0
Dn Type=3
Dn Slope=0.005
Boundary for River Rch & Prof#=Elm 01 05,Reach-1,2
Up Type=0
Dn Type=3
Dn Slope=0.005
Boundary for River Rch & Prof#=Elm 01 05,Reach-1,3
Up Type=0
Dn Type=3
Dn Slope=0.005
Boundary for River Rch & Prof#=Elm 01 05,Reach-1,4
Up Type=0
Dn Type=3
Dn Slope=0.005
Boundary for River Rch & Prof#=Elm 01 05,Reach-1,5
Up Type=0
Dn Type=3
Dn Slope=0.005
Boundary for River Rch & Prof#=Elm 01 05,Reach-1,6
Up Type=0
Dn Type=3
Dn Slope=0.005
Boundary for River Rch & Prof#=Elm 01 05,Reach-1,7
Up Type=0
Dn Type=3
Dn Slope=0.005

--- Elm 01 05.g01 (geometry) ---

Geom Title=Existing Conditions

River Reach=Elm 01 05,Reach-1
Reach XY= 30
      1550955.00      6782988.00      1551115.19      6782937.45
      1551254.90      6783030.67      1551320.16      6782988.66
      1551649.10      6782990.23      1551906.50      6783184.38
      1552151.69      6783279.93      1552248.88      6783239.84
      1552461.06      6783346.14      1552648.55      6783580.25
      1552761.43      6783595.79      1552813.35      6783684.81
      1553049.53      6783743.26      1553152.82      6783893.45
      1553162.68      6784144.52      1553394.49      6784278.19
      1553412.86      6784394.17      1553749.48      6784785.57
      1553808.69      6784979.80      1554160.45      6785382.79
      1554357.70      6785393.36      1554460.44      6785536.34
      1554689.78      6785488.50      1555014.81      6785598.51
      1555101.39      6785689.48      1555260.77      6786140.53
      1555351.89      6786196.32      1555358.08      6786329.71
      1555556.72      6786434.66      1556055.00      6786288.00

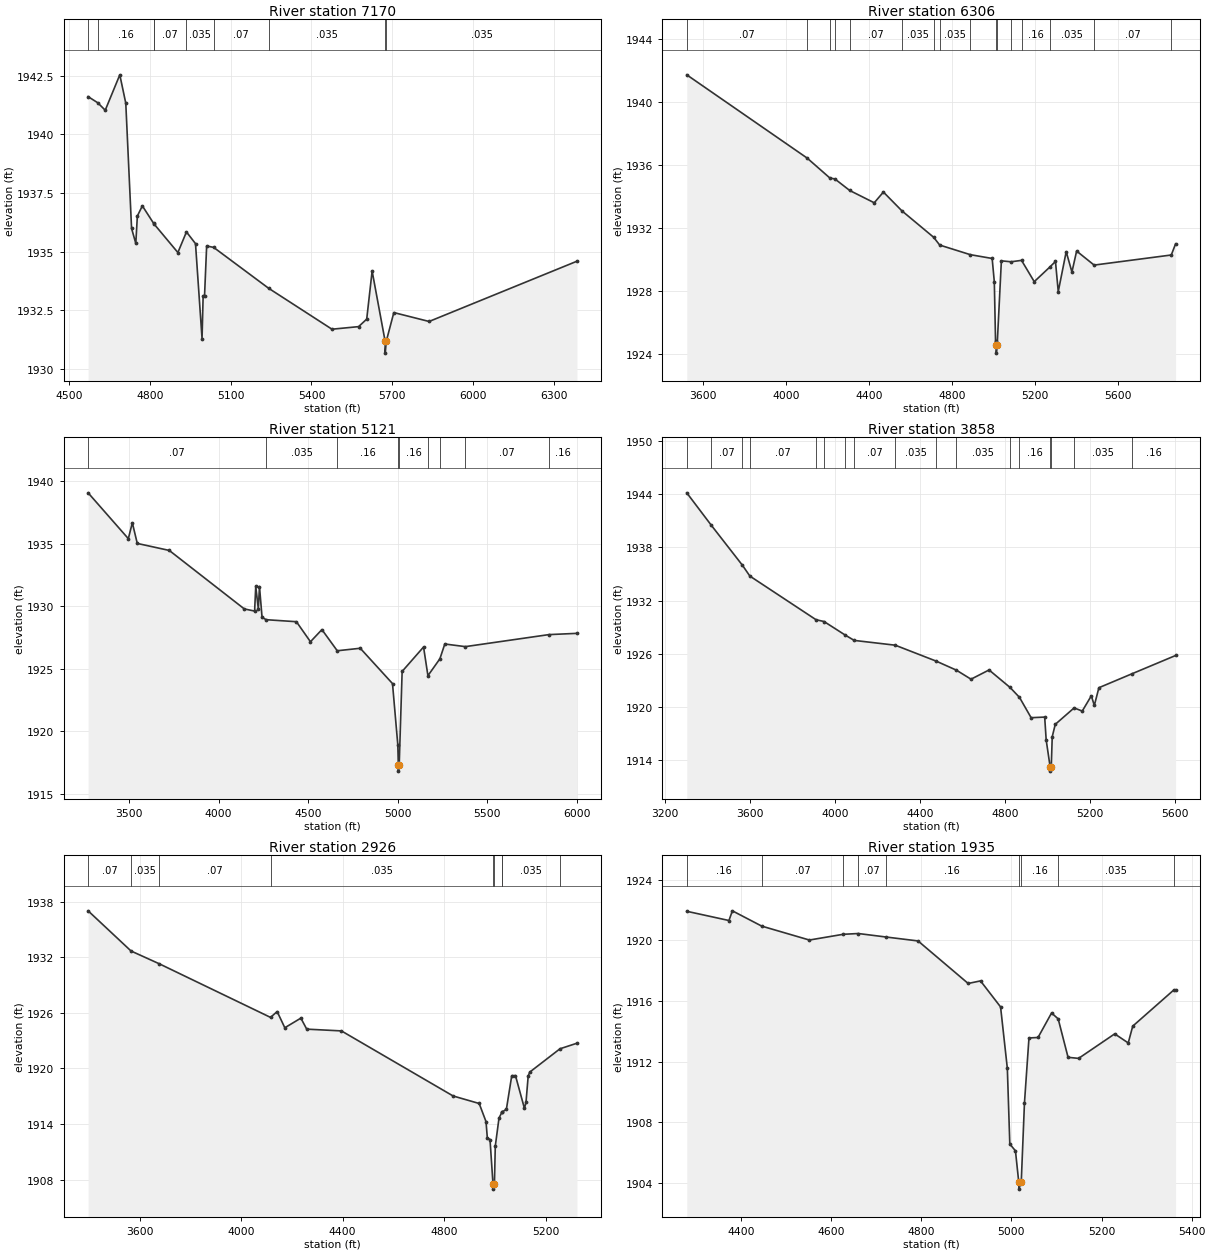
Type RM Length L Ch R = 1,7170,864,864,864
BEGIN DESCRIPTION:
225
END DESCRIPTION:
XS GIS Cut Line= 3
      1550904.98      6783338.04      1551062.99      6782938.67
      1551230.00      6781562.97
#Sta/Elev= 30
  4570.5 1941.61  4606.1 1941.35  4634.1 1941.03  4688.2 1942.54  4710.4 1941.33
  4731.9 1935.99  4747.6 1935.35  4753.4 1936.52  4772.0 1936.95  4814.1 1936.20
  4814.5 1936.19  4903.9 1934.96  4935.7 1935.84  4969.3 1935.34  4993.6 1931.29
  4997.7 1933.12  5002.9 1933.12  5010.7 1935.24  5036.7 1935.18  5240.4 1933.44
  5476.1 1931.69  5574.9 1931.80  5605.1 1932.12  5625.2 1934.17  5673.6 1931.17
  5673.8 1930.67  5677.6 1931.17  5705.8 1932.40  5836.8 1932.02  6385.8 1934.59
#Mann=9,-1,0
  4570.5    0.07       0  4606.1    0.16       0  4814.1   0.035       0
  4814.5    0.07       0  4935.7   0.035       0  5036.7    0.07       0
  5240.4   0.035       0  5673.6   0.035       0  5677.6   0.035       0
Bank Sta=5673.6,5677.6
Exp/Cntr=0.3,0.1

Type RM Length L Ch R = 1,6306,1185,1185,1185
BEGIN DESCRIPTION:
829
END DESCRIPTION:
XS GIS Cut Line= 4
      1551139.19      6784419.76      1551812.82      6783135.00
      1552157.83      6782485.92      1552248.63      6782343.90
#Sta/Elev= 30
  3521.9 1941.70  4102.0 1936.42  4211.1 1935.16  4235.3 1935.10  4306.6 1934.37
  4424.8 1933.59  4468.9 1934.27  4557.9 1933.08  4711.2 1931.40  4740.0 1930.91
  4887.7 1930.30  4992.7 1930.06  5003.1 1928.58  5009.0 1924.82  5012.4 1924.56
  5012.7 1924.06  5016.8 1924.56  5037.1 1929.91  5083.7 1929.85  5134.2 1929.94
  5195.4 1928.59  5269.1 1929.50  5297.6 1929.87  5311.0 1927.96  5349.3 1930.49
  5376.9 1929.20  5399.5 1930.53  5483.8 1929.64  5855.4 1930.28  5876.2 1930.99
#Mann=16,-1,0
  3521.9    0.07       0  4102.0   0.035       0  4211.1    0.07       0
  4235.3   0.035       0  4306.6    0.07       0  4557.9   0.035       0
  4711.2    0.07       0  4740.0   0.035       0  4887.7    0.07       0
  5012.4    0.07       0  5016.8    0.07       0  5083.7   0.035       0
  5134.2    0.16       0  5269.1   0.035       0  5483.8    0.07       0
  5855.4    0.16       0
Bank Sta=5012.4,5016.8
Exp/Cntr=0.3,0.1

Type RM Length L Ch R = 1,5121,1263,1263,1263
BEGIN DESCRIPTION:
828
END DESCRIPTION:
XS GIS Cut Line= 3
      1551701.73      6784961.36      1552764.21      6783648.89
      1553153.10      6782683.61
#Sta/Elev= 30
  3271.2 1939.05  3495.8 1935.39  3518.1 1936.66  3545.7 1935.01  3724.4 1934.45
  4143.3 1929.78  4200.8 1929.61  4207.2 1931.58  4221.6 1929.78  4228.0 1931.57
  4242.4 1929.11  4265.5 1928.92  4434.3 1928.76  4512.6 1927.16  4576.6 1928.13
  4662.2 1926.44  4790.7 1926.64  4970.7 1923.82  5000.3 1918.93  5003.2 1917.33
  5003.6 1916.83  5008.1 1917.33  5024.5 1924.79  5144.1 1926.74  5168.5 1924.45
  5235.3 1925.80  5262.7 1926.98  5377.5 1926.77  5843.8 1927.73  6000.5 1927.83
#Mann=9,-1,0
  3271.2    0.07       0  4265.5   0.035       0  4662.2    0.16       0
  5003.2    0.07       0  5008.1    0.16       0  5168.5   0.063       0
  5235.3   0.035       0  5377.5    0.07       0  5843.8    0.16       0
Bank Sta=5003.2,5008.1
Exp/Cntr=0.3,0.1

Type RM Length L Ch R = 1,3858,932,932,932
BEGIN DESCRIPTION:
224
END DESCRIPTION:
XS GIS Cut Line= 3
      1552255.02      6785637.98      1553472.36      6784454.38
      1553879.99      6784013.01
#Sta/Elev= 30
  3302.1 1944.15  3417.9 1940.48  3563.8 1935.99  3598.8 1934.77  3910.0 1929.85
  3947.5 1929.65  4046.6 1928.13  4089.4 1927.52  4282.5 1926.98  4474.5 1925.19
  4569.8 1924.17  4638.7 1923.15  4723.6 1924.19  4822.3 1922.22  4866.7 1921.10
  4921.4 1918.81  4985.2 1918.88  4992.2 1916.30  5010.7 1913.29  5011.1 1912.79
  5016.1 1913.29  5020.7 1916.67  5034.9 1918.06  5123.4 1919.91  5161.9 1919.56
  5204.5 1921.28  5218.6 1920.19  5240.1 1922.19  5395.7 1923.76  5600.8 1925.82
#Mann=17,-1,0
  3302.1   0.035       0  3417.9    0.07       0  3563.8   0.035       0
  3598.8    0.07       0  3910.0   0.035       0  3947.5    0.07       0
  4046.6   0.035       0  4089.4    0.07       0  4282.5   0.035       0
  4474.5    0.07       0  4569.8   0.035       0  4822.3    0.07       0
  4866.7    0.16       0  5010.7    0.07       0  5016.1    0.16       0
  5123.4   0.035       0  5395.7    0.16       0
Bank Sta=5010.7,5016.1
Exp/Cntr=0.3,0.1

Type RM Length L Ch R = 1,2926,991,991,991
BEGIN DESCRIPTION:
830
END DESCRIPTION:
XS GIS Cut Line= 3
      1552653.10      6786058.62      1553972.54      6785197.50
      1554180.35      6784913.49
#Sta/Elev= 30
  3396.5 1937.03  3565.8 1932.69  3677.1 1931.31  4115.8 1925.52  4141.9 1926.15
  4172.1 1924.40  4235.4 1925.44  4258.5 1924.25  4395.3 1924.06  4835.8 1917.03
  4938.5 1916.22  4965.5 1914.26  4970.6 1912.50  4981.2 1912.33  4993.1 1907.47
  4993.5 1906.97  4998.6 1907.47  5002.0 1911.61  5016.7 1914.65  5027.8 1915.26
  5028.2 1915.28  5045.8 1915.60  5066.9 1919.22  5081.6 1919.23  5117.1 1915.68
  5123.3 1916.40  5131.7 1919.18  5137.9 1919.61  5257.2 1922.13  5324.0 1922.73
#Mann=9,-1,0
  3396.5    0.07       0  3565.8   0.035       0  3677.1    0.07       0
  4115.8   0.035       0  4993.1   0.035       0  4998.6   0.035       0
  5027.8    0.16       0  5028.2   0.035       0  5257.2    0.16       0
Bank Sta=4993.1,4998.6
Exp/Cntr=0.3,0.1

Type RM Length L Ch R = 1,1935,1005,1005,1005
BEGIN DESCRIPTION:
223
END DESCRIPTION:
XS GIS Cut Line= 3
      1554395.36      6786156.42      1554745.37      6785527.10
      1554730.00      6785163.03
#Sta/Elev= 30
  4279.9 1921.93  4373.5 1921.32  4381.1 1921.96  4446.2 1920.95  4551.9 1920.03
  4627.1 1920.41  4660.6 1920.46  4721.9 1920.23  4793.0 1919.97  4904.2 1917.16
  4931.6 1917.33  4976.1 1915.61  4991.1 1911.55  4996.6 1906.55  5009.1 1906.10
  5016.3 1904.07  5016.8 1903.57  5022.0 1904.07  5029.1 1909.27  5039.1 1913.56
  5059.2 1913.59  5089.2 1915.21  5103.9 1914.82  5125.8 1912.28  5149.2 1912.21
  5229.3 1913.83  5259.3 1913.23  5269.3 1914.34  5360.8 1916.74  5364.4 1916.74
#Mann=9,-1,0
  4279.9    0.16       0  4446.2    0.07       0  4627.1    0.16       0
  4660.6    0.07       0  4721.9    0.16       0  5016.3    0.07       0
  5022.0    0.16       0  5103.9   0.035       0  5360.8    0.07       0
Bank Sta=5016.3,5022
Exp/Cntr=0.3,0.1

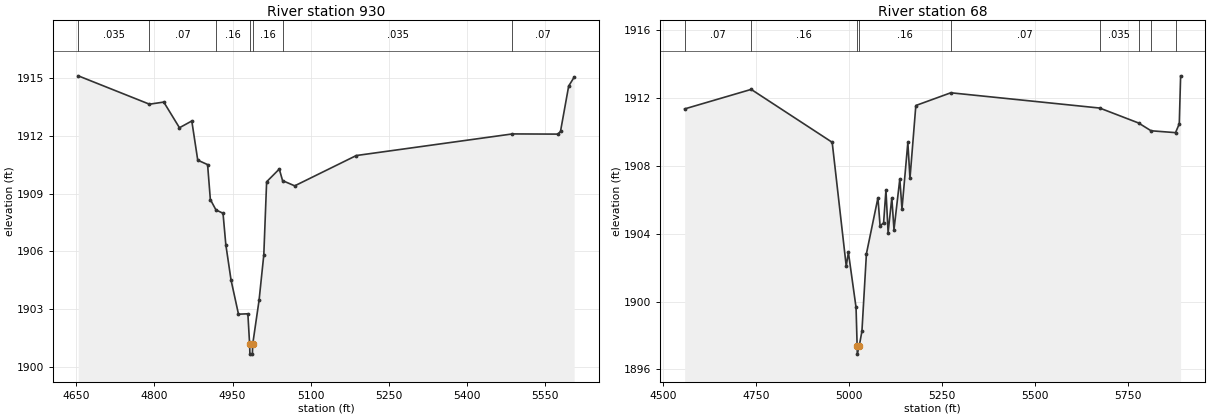
Type RM Length L Ch R = 1,930,862,862,862
BEGIN DESCRIPTION:
876
END DESCRIPTION:
XS GIS Cut Line= 3
      1555206.97      6786510.54      1555378.26      6786080.01
      1555253.27      6785607.83
#Sta/Elev= 30
  4653.8 1915.10  4790.5 1913.63  4818.0 1913.74  4848.1 1912.41  4871.8 1912.76
  4883.2 1910.73  4902.1 1910.50  4907.4 1908.69  4918.2 1908.15  4931.7 1907.98
  4937.1 1906.35  4947.1 1904.52  4961.4 1902.75  4979.4 1902.77  4982.8 1901.18
  4983.3 1900.68  4988.1 1900.68  4988.6 1901.18  5000.9 1903.47  5010.0 1905.83
  5015.4 1909.61  5039.7 1910.27  5046.0 1909.67  5069.3 1909.40  5187.5 1910.97
  5487.2 1912.09  5574.3 1912.08  5579.4 1912.22  5595.1 1914.57  5605.6 1915.03
#Mann=7,-1,0
  4653.8   0.035       0  4790.5    0.07       0  4918.2    0.16       0
  4982.8    0.07       0  4988.6    0.16       0  5046.0   0.035       0
  5487.2    0.07       0
Bank Sta=4982.8,4988.6
Exp/Cntr=0.3,0.1

Type RM Length L Ch R = 1,68,0,0,0
BEGIN DESCRIPTION:
222
END DESCRIPTION:
XS GIS Cut Line= 4
      1555778.10      6786690.56      1555993.38      6786301.67
      1555580.00      6786063.00      1555447.78      6785672.82
#Sta/Elev= 30
  4557.9 1911.36  4736.8 1912.51  4954.6 1909.39  4992.4 1902.09  4998.2 1902.90
  5018.8 1899.65  5021.7 1897.40  5022.2 1896.90  5027.5 1897.40  5034.6 1898.25
  5046.7 1902.82  5077.7 1906.12  5083.4 1904.46  5092.9 1904.64  5099.2 1906.58
  5105.0 1904.07  5115.0 1906.12  5120.8 1904.24  5136.5 1907.23  5142.3 1905.46
  5158.1 1909.38  5163.8 1907.26  5179.6 1911.56  5273.6 1912.31  5674.1 1911.41
  5778.5 1910.53  5812.2 1910.07  5878.0 1909.96  5888.1 1910.48  5891.7 1913.31
#Mann=9,-1,0
  4557.9    0.07       0  4736.8    0.16       0  5021.7    0.07       0
  5027.5    0.16       0  5273.6    0.07       0  5674.1   0.035       0
  5778.5    0.07       0  5812.2   0.035       0  5878.0    0.07       0
Bank Sta=5021.7,5027.5
Exp/Cntr=0.3,0.1

Chan Stop Cuts=-1