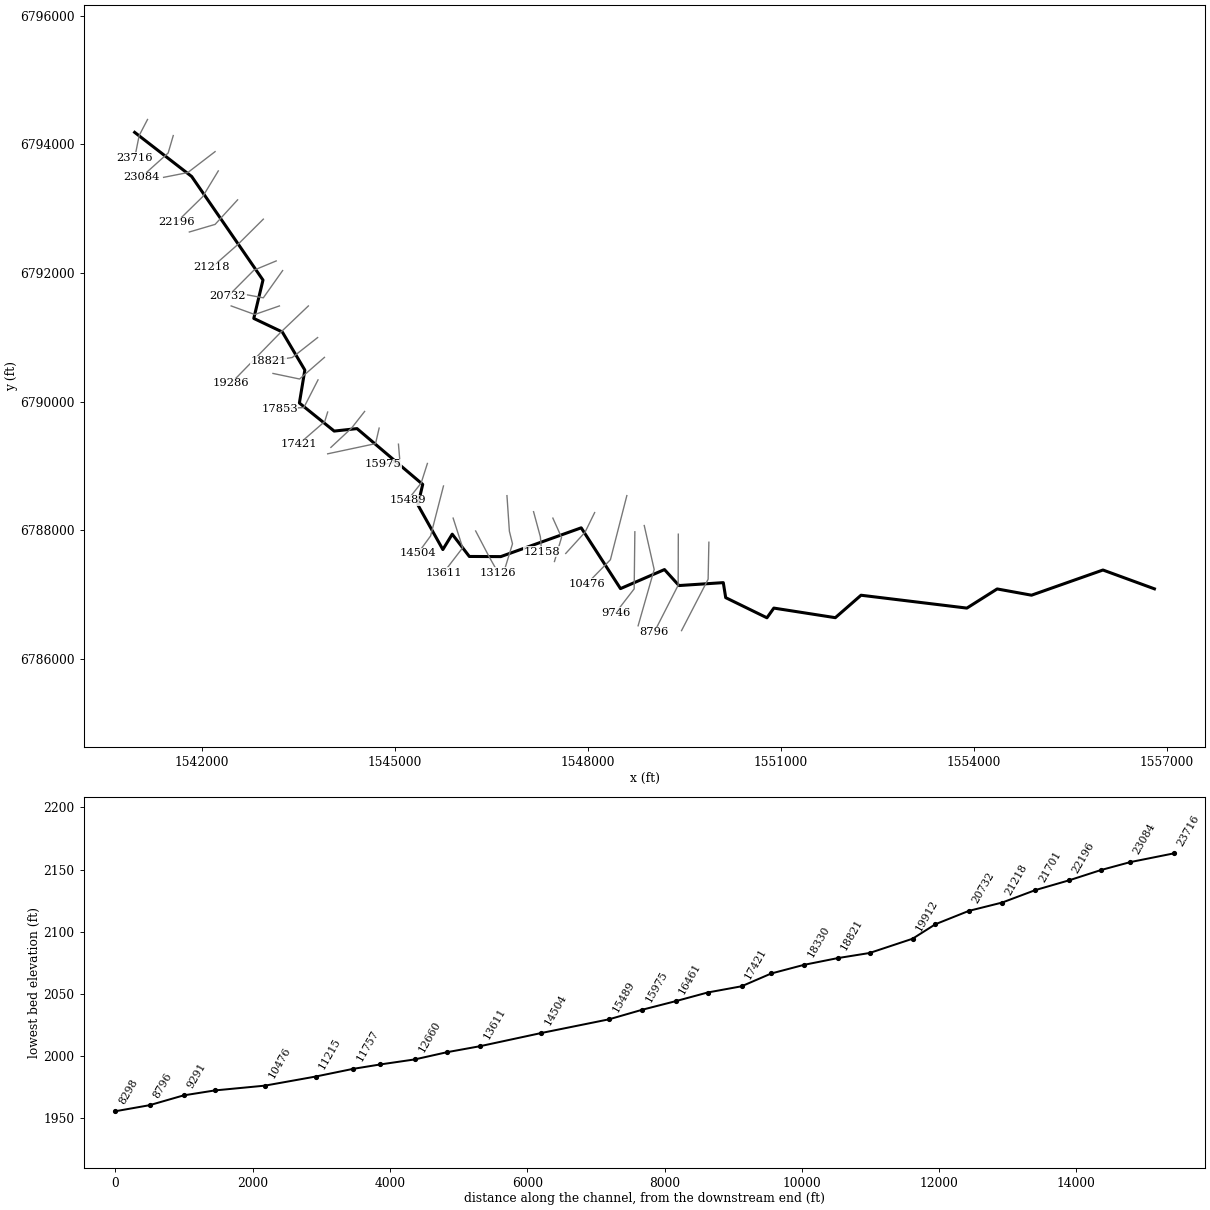
--- Elm 01 06.prj (project) ---

Proj Title=Elm 01 06 Base Level Engineering
Current Plan=p01
Default Exp/Contr=0.3,0.1
English Units
Geom File=g01
Flow File=f01
Plan File=p01
Y Axis Title=Elevation
X Axis Title(PF)=Main Channel Distance
X Axis Title(XS)=Station
BEGIN DESCRIPTION:
Elm 01 06
END DESCRIPTION:
DSS Export Rating Curves= 0
DSS Export Rating Curve Sorted= 0
DSS Export Volume Flow Curves= 0
DXF OffsetX= 0
DXF OffsetY= 0
DXF ScaleX= 1
DXF ScaleY= 10

--- Elm 01 06.p01 (plan) ---

Plan Title=Multiple Run
Program Version=4.10
Short Identifier=Multiple
Geom File=g01
Flow File=f01
Subcritical Flow
K Sum by GR= 0
Std Step Tol= 0.01
Critical Tol= 0.01
Num of Std Step Trials= 20
Max Error Tol= 0.3
Flow Tol Ratio= 0.001
Split Flow NTrial= 30
Split Flow Tol= 0.02
Split Flow Ratio= 0.02
Log Output Level= 0
Friction Slope Method= 1
Unsteady Friction Slope Method= 2
Unsteady Bridges Friction Slope Method= 1
Parabolic Critical Depth
Global Vel Dist= 1 , 1 , 1
Global Log Level= 0
CheckData=True
Encroach Param=-1 ,0,0, 0
BEGIN DESCRIPTION:
Multiple Run
END DESCRIPTION:
Computation Interval=1HOUR
Output Interval=1HOUR
Run HTab= 0
Run UNet= 0
Run PostProcess= 0
Run WQNet= 0
UNET Theta= 1
UNET Theta Warmup= 1
UNET ZTol= 0.02
UNET ZSATol= 0.05
UNET MxIter= 20
UNET MaxInSteps= 0
UNET DtIC= 0
UNET DtMin= 0
UNET MaxCRTS= 20
UNET WFStab= 2
UNET SFStab= 1
UNET WFX= 1
UNET SFX= 1
UNET DSS MLevel= 4
UNET DZMax Abort= 100
UNET Convert EG Bridges= 0
UNET Use Existing IB Tables=-1
UNET Froude Reduction=False
UNET Froude Limit= 1
UNET Froude Power= 10
UNET Time Slicing=0,0, 5
UNET Junction Losses=0
Instantaneous Interval=1HOUR
Write IC File= 0
Write IC File at Sim End=0
Echo Input=False
Echo Parameters=False
Echo Output=False
Write Detailed= 0
WQ AD Non Conservative
WQ ULTIMATE=-1
WQ Max Comp Step=1HOUR
WQ Output Interval=15MIN
WQ Output Selected Increments= 0
WQ Output face flow=0
WQ Output face velocity=0
WQ Output face area=0
WQ Output face dispersion=0
WQ Output cell volume=0
WQ Output cell surface area=0
WQ Output cell continuity=0
WQ Output cumulative cell continuity=0
WQ Output face conc=0
WQ Output face dconc_dx=0
WQ Output face courant=0
WQ Output face peclet=0
WQ Output face adv mass=0
WQ Output face disp mass=0
WQ Output cell mass=0
WQ Output cell source sink temp=0
WQ Output cell source sink nsm=0
WQ Output MaxMinRange=-1
WQ Daily Max Min Mean=-1
WQ Daily Range=0
WQ Daily Time=0
WQ Create Restart=0
WQ Fixed Restart=0
WQ System Summary=0
WQ Use Fixed Temperature=0
Sorting and Armoring Iterations= 10
XS Update Threshold= 0.02
Hydraulics Update Threshold= 0.02
Energy Slope Method= 1
Volume Change Method= 0
XS Weighting Method= 0
Number of US Weighted Cross Sections= 1
Number of DS Weighted Cross Sections= 1
Upstream XS Weight=0.25
Main XS Weight=0.5
Downstream XS Weight=0.25
Number of DS XS's Weighted with US Boundary= 1
Upstream Boundary Weight= 1
Weight of XSs Associated with US Boundary= 0
Number of US XS's Weighted with DS Boundary= 1
Downstream Boundary Weight= 0.5
Weight of XSs Associated with DS Boundary= 0.5
Sediment Output Level= 4
Mass or Volume Output= 0
Output Increment Type= 1
Profile and TS Output Increment= 10
XS Output Flag= 0
XS Output Increment= 10
Disregard all LS=0
Disregard all Conn=0
Disregard all Breaches=0
Disregard all Pumps=0

--- Elm 01 06.f01 (steady flow) ---

Flow Title=Multiple
Number of Profiles=7
Profile Names=10-year,25-year,50-year,1pct_min,100-year,1pct_plu,500-year
River Rch & RM= Elm 01 06,Reach-1,23716
     394     573     729     577     925    1270    1500
River Rch & RM= Elm 01 06,Reach-1,23084
     601     891    1150     918    1470    2020    2440
River Rch & RM= Elm 01 06,Reach-1,18821
     701    1040    1340    1070    1720    2370    2860
River Rch & RM= Elm 01 06,Reach-1,12158
     785    1170    1510    1210    1940    2660    3230
River Rch & RM= Elm 01 06,Reach-1,5953
    1160    1750    2280    1840    2950    4050    4980
Boundary for River Rch & Prof#=Elm 01 06,Reach-1,1
Up Type=0
Dn Type=3
Dn Slope=0.005
Boundary for River Rch & Prof#=Elm 01 06,Reach-1,2
Up Type=0
Dn Type=3
Dn Slope=0.005
Boundary for River Rch & Prof#=Elm 01 06,Reach-1,3
Up Type=0
Dn Type=3
Dn Slope=0.005
Boundary for River Rch & Prof#=Elm 01 06,Reach-1,4
Up Type=0
Dn Type=3
Dn Slope=0.005
Boundary for River Rch & Prof#=Elm 01 06,Reach-1,5
Up Type=0
Dn Type=3
Dn Slope=0.005
Boundary for River Rch & Prof#=Elm 01 06,Reach-1,6
Up Type=0
Dn Type=3
Dn Slope=0.005
Boundary for River Rch & Prof#=Elm 01 06,Reach-1,7
Up Type=0
Dn Type=3
Dn Slope=0.005

--- Elm 01 06.g01 (geometry) ---

Geom Title=Existing Conditions
Program Version=4.10

River Reach=Elm 01 06       ,Reach-1
Reach XY= 30
        1540955.        6794188.      1541841.37      6793501.21
      1542949.54      6791890.45       1542806.5      6791293.87
      1543249.89      6791082.89      1543600.04      6790490.54
      1543515.47      6789978.17      1544056.47      6789541.53
      1544411.18      6789580.18      1545432.29       6788711.9
      1545356.99      6788393.39      1545745.15      6787698.89
      1545891.01      6787938.04      1546156.45      6787591.53
      1546645.42       6787589.2      1547895.59      6788036.87
      1548506.22      6787091.44      1549189.85      6787387.62
      1549415.47      6787138.93      1550103.98      6787184.39
      1550141.35      6786950.95      1550782.43      6786637.51
      1550889.68      6786788.49      1551845.37      6786639.35
      1552244.81      6786988.46      1553889.84      6786788.37
      1554360.63      6787086.26      1554894.56      6786989.05
      1556004.92       6787380.7        1556805.        6787088.

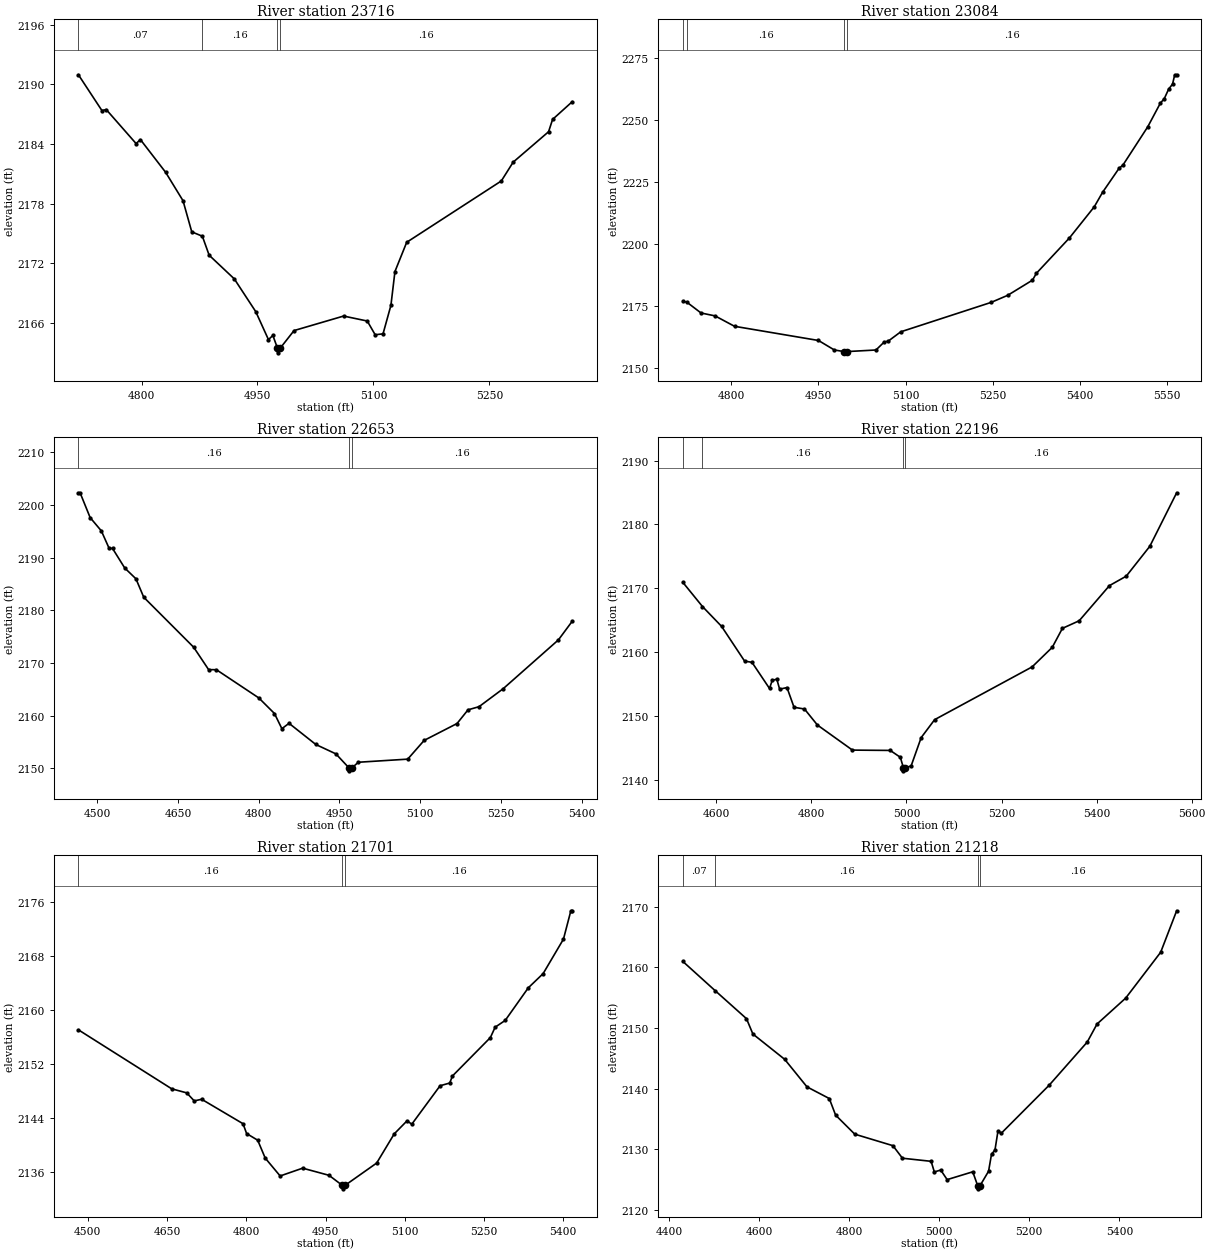
Type RM Length L Ch R = 1 ,23716   ,632,632,632
BEGIN DESCRIPTION:
54
END DESCRIPTION:
XS GIS Cut Line= 3
      1541155.02      6794388.03       1541025.1       6794138.2
      1540955.01      6793788.04
#Sta/Elev= 30
  4718.4 2190.95  4748.8 2187.35  4754.4 2187.45    4793 2184.03  4798.6 2184.43
  4831.2 2181.14  4853.7 2178.28    4865 2175.15  4878.7 2174.71  4887.5  2172.8
    4920 2170.42  4947.8 2167.12  4964.2 2164.31  4969.9 2164.73  4975.7 2163.48
  4975.9 2162.98  4979.7 2163.48  4997.3 2165.22  5061.4 2166.68    5092 2166.18
  5102.2  2164.8  5112.4 2164.89  5122.6 2167.76  5127.8 2171.16    5143  2174.1
  5265.4 2180.27  5280.7 2182.16  5326.5 2185.22  5331.7 2186.46  5357.1 2188.24
#Mann= 4 ,-1 , 0
  4718.4     .07       0  4878.7     .16       0  4975.7     .07       0
  4979.7     .16       0
Bank Sta=4975.7,4979.7
XS Rating Curve= 0 ,0
Exp/Cntr=0.3,0.1

Type RM Length L Ch R = 1 ,23084   ,431,431,431
BEGIN DESCRIPTION:
53
END DESCRIPTION:
XS GIS Cut Line= 3
      1541554.99      6794137.98      1541475.74      6793866.62
      1541055.01      6793488.01
#Sta/Elev= 30
  4717.3 2176.79  4724.1 2176.47  4748.5 2172.09  4772.7 2170.91  4806.1 2166.71
  4950.4 2160.98  4977.7 2157.14  4994.7 2156.49  4994.9 2155.99  4998.7 2156.49
  5049.2 2157.14  5063.4 2160.37  5070.1 2160.69  5091.8 2164.48  5247.2 2176.37
  5275.6 2179.22  5318.2 2185.35    5325 2188.14  5381.8 2202.42  5424.4 2214.98
  5438.6  2220.8    5467 2230.52  5473.7 2231.84  5516.3 2247.28    5538 2256.85
  5544.7 2258.64  5552.2 2262.49  5558.9 2264.53  5562.7  2268.3    5566  2268.3
#Mann= 4 ,-1 , 0
  4717.3     .07       0  4724.1     .16       0  4994.7     .07       0
  4998.7     .16       0
Bank Sta=4994.7,4998.7
XS Rating Curve= 0 ,0
Exp/Cntr=0.3,0.1

Type RM Length L Ch R = 1 ,22653   ,457,457,457
BEGIN DESCRIPTION:
52
END DESCRIPTION:
XS GIS Cut Line= 3
      1542204.98      6793887.99      1541780.43      6793562.11
      1541404.98        6793488.
#Sta/Elev= 30
  4464.8 2202.31  4467.9 2202.31  4486.6  2197.6  4507.4 2195.08  4521.9 2191.76
  4528.2 2191.75  4550.9 2188.03  4571.7 2185.99  4586.2 2182.49  4679.1 2172.99
  4706.8 2168.75  4721.3 2168.73  4800.2 2163.37  4829.2 2160.42    4843 2157.54
  4856.3 2158.56  4906.1 2154.54  4943.4 2152.76  4968.3 2150.04  4968.6 2149.54
  4972.7 2150.04    4985 2151.17  5076.9 2151.76  5107.5 2155.32  5168.6 2158.52
    5189 2161.12  5209.4 2161.71  5254.4 2165.13    5357 2174.39  5382.7 2177.93
#Mann= 3 ,-1 , 0
  4464.8     .16       0  4968.3     .07       0  4972.7     .16       0
Bank Sta=4968.3,4972.7
XS Rating Curve= 0 ,0
Exp/Cntr=0.3,0.1

Type RM Length L Ch R = 1 ,22196   ,495,495,495
BEGIN DESCRIPTION:
51
END DESCRIPTION:
XS GIS Cut Line= 3
      1542255.01      6793588.02      1542011.08       6793185.8
      1541604.97      6792787.97
#Sta/Elev= 30
  4529.6 2170.93  4570.9 2167.14    4611 2164.04  4659.5 2158.59    4675  2158.4
  4711.9  2154.3  4717.7 2155.58  4727.3 2155.75  4733.2 2154.19  4748.7 2154.44
  4763.5 2151.35  4785.5 2151.08  4812.7 2148.57  4886.4 2144.64  4965.9 2144.59
  4987.2 2143.51  4993.5 2141.89  4993.8 2141.39    4998 2141.89  5009.8 2142.15
    5031  2146.6  5059.3 2149.41  5264.4 2157.68  5306.8 2160.75  5328.1 2163.72
  5363.4 2164.91  5427.1 2170.42  5462.4  2171.9    5512 2176.58  5568.5 2184.97
#Mann= 4 ,-1 , 0
  4529.6     .07       0  4570.9     .16       0  4993.5     .07       0
    4998     .16       0
Bank Sta=4993.5,4998
XS Rating Curve= 0 ,0
Exp/Cntr=0.3,0.1

Type RM Length L Ch R = 1 ,21701   ,483,483,483
BEGIN DESCRIPTION:
50
END DESCRIPTION:
XS GIS Cut Line= 3
      1542555.03      6793138.03      1542205.11      6792756.23
      1541805.01        6792638.
#Sta/Elev= 30
  4482.1 2157.08  4658.8 2148.32  4687.2 2147.72  4701.4 2146.53  4715.5 2146.77
  4793.8 2143.14  4800.6 2141.68  4821.6 2140.69  4835.8 2138.04  4864.1 2135.38
  4906.7 2136.54  4956.6 2135.48  4982.1 2133.97  4982.4 2133.47  4986.7 2133.97
  5046.9  2137.3  5080.1 2141.63  5104.4 2143.57  5113.4 2143.07    5167 2148.78
  5185.2 2149.18  5190.4 2150.23  5262.2 2155.93  5271.2 2157.47  5290.3 2158.48
    5334 2163.32  5362.1 2165.43  5400.6 2170.55  5414.6 2174.76  5417.2 2174.76
#Mann= 3 ,-1 , 0
  4482.1     .16       0  4982.1     .07       0  4986.7     .16       0
Bank Sta=4982.1,4986.7
XS Rating Curve= 0 ,0
Exp/Cntr=0.3,0.1

Type RM Length L Ch R = 1 ,21218   ,486,486,486
BEGIN DESCRIPTION:
49
END DESCRIPTION:
XS GIS Cut Line= 3
      1542955.03      6792838.03      1542551.03      6792436.35
      1542155.03      6792088.02
#Sta/Elev= 30
  4430.3 2160.97  4502.7 2156.11  4571.7 2151.53  4585.9    2149  4656.6 2144.82
  4706.1 2140.28  4755.6 2138.36  4769.7 2135.62  4812.2 2132.48    4897 2130.58
  4918.2 2128.51  4981.9    2128    4989 2126.25  5003.2 2126.56  5017.5 2124.98
  5074.4 2126.27  5085.4 2123.96  5085.8 2123.46  5090.4 2123.96  5109.5 2126.36
  5116.1 2129.19  5123.7 2129.85  5130.4 2132.99  5137.9 2132.64  5244.2 2140.56
  5328.7 2147.67  5350.5 2150.65  5414.1 2154.92  5491.9 2162.49  5527.4 2169.33
#Mann= 4 ,-1 , 0
  4430.3     .07       0  4502.7     .16       0  5085.4     .07       0
  5090.4     .16       0
Bank Sta=5085.4,5090.4
XS Rating Curve= 0 ,0
Exp/Cntr=0.3,0.1

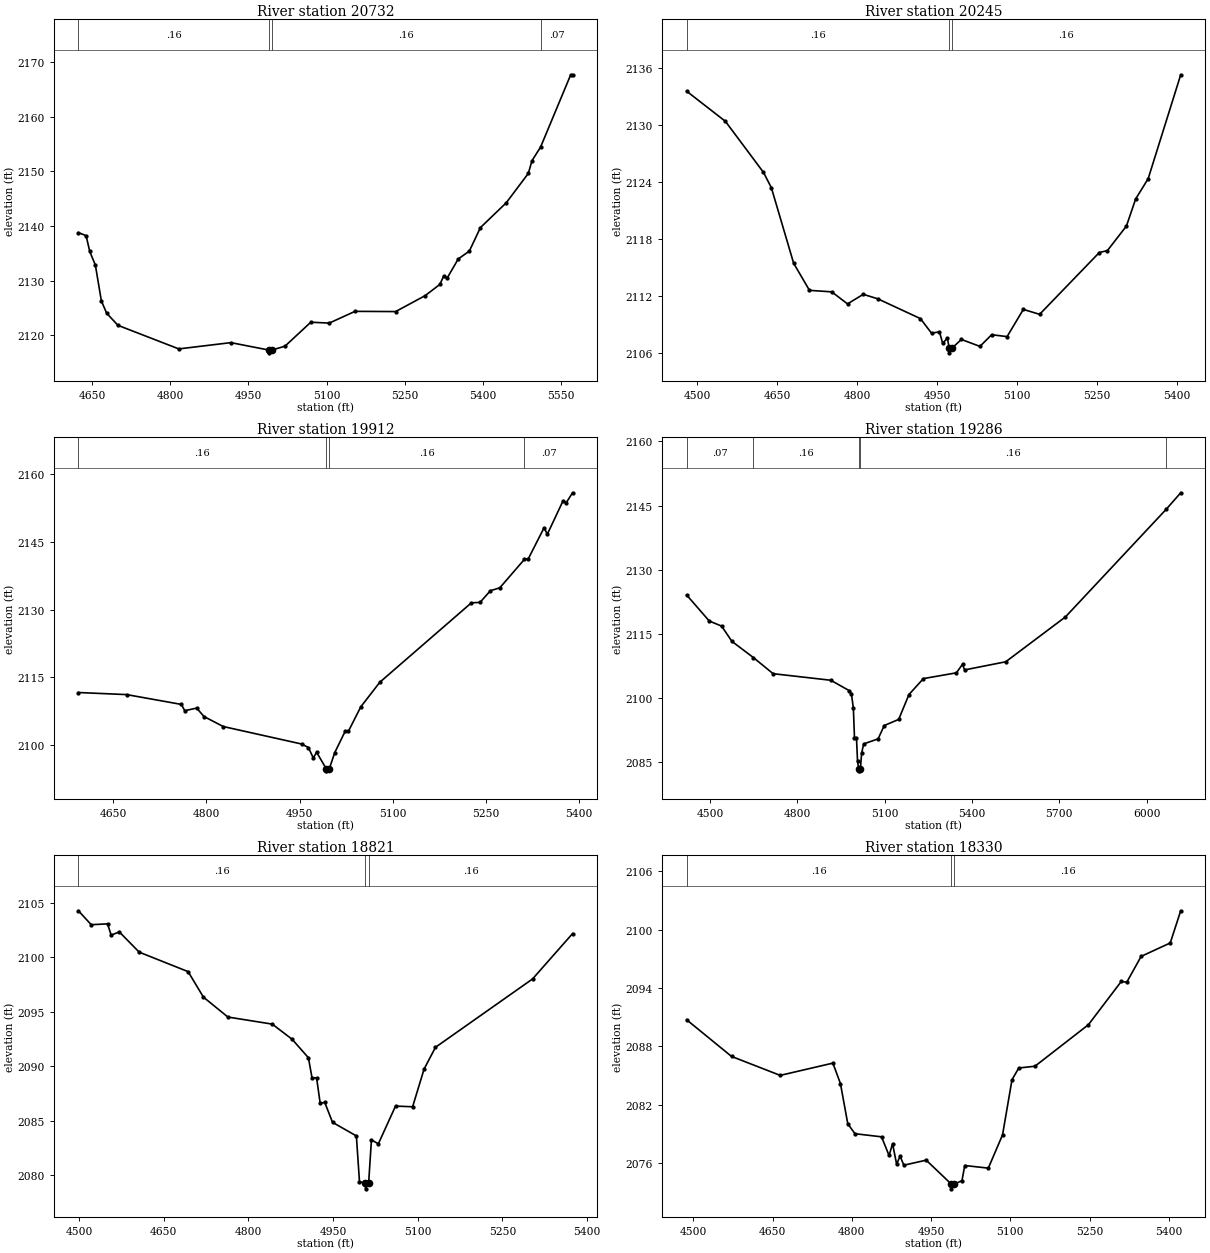
Type RM Length L Ch R = 1 ,20732   ,487,487,487
BEGIN DESCRIPTION:
48
END DESCRIPTION:
XS GIS Cut Line= 3
      1543155.04      6792188.02      1542807.64      6792043.64
      1542405.03      6791638.03
#Sta/Elev= 30
  4623.8 2138.77  4638.5 2138.22  4645.5 2135.32  4656.3 2132.82  4667.8 2126.26
    4678    2124  4699.6 2121.79  4816.3 2117.47  4916.2 2118.62  4989.5 2117.25
  4989.9 2116.75  4994.6 2117.25    5020 2117.97  5069.5 2122.36  5104.9  2122.2
  5154.3 2124.35  5232.2 2124.31  5288.7 2127.22    5317 2129.28  5324.1 2130.75
  5331.2 2130.47  5352.3 2133.95  5373.6 2135.39  5394.8 2139.69  5444.3 2144.23
  5486.7 2149.62  5493.8 2151.96  5510.3 2154.46    5568 2167.69  5571.5 2167.69
#Mann= 4 ,-1 , 0
  4623.8     .16       0  4989.5     .07       0  4994.6     .16       0
  5510.3     .07       0
Bank Sta=4989.5,4994.6
XS Rating Curve= 0 ,0
Exp/Cntr=0.3,0.1

Type RM Length L Ch R = 1 ,20245   ,333,333,333
BEGIN DESCRIPTION:
47
END DESCRIPTION:
XS GIS Cut Line= 3
      1543255.02      6792038.03      1542954.65      6791614.17
      1542555.02        6791688.
#Sta/Elev= 30
  4480.5  2133.6  4553.2 2130.42  4624.5 2125.04  4639.3 2123.42  4681.1 2115.45
  4710.7  2112.6  4752.5 2112.44    4782 2111.17  4811.5 2112.18  4838.6 2111.71
  4918.6 2109.62  4939.5 2108.08  4954.3 2108.23  4960.4    2107  4969.1 2107.57
  4972.6 2106.51    4973 2106.01  4977.8 2106.51  4995.4 2107.42  5030.2 2106.69
  5052.1 2107.92    5081 2107.72  5111.5 2110.59    5142 2110.07  5253.9 2116.59
    5269 2116.79  5304.7 2119.38  5321.9 2122.23  5345.4 2124.37  5406.4 2135.33
#Mann= 3 ,-1 , 0
  4480.5     .16       0  4972.6     .07       0  4977.8     .16       0
Bank Sta=4972.6,4977.8
XS Rating Curve= 0 ,0
Exp/Cntr=0.3,0.1

Type RM Length L Ch R = 1 ,19912   ,626,626,626
BEGIN DESCRIPTION:
46
END DESCRIPTION:
XS GIS Cut Line= 3
        1543205.        6791488.      1542821.19      6791354.69
        1542455.        6791488.
#Sta/Elev= 30
  4593.7 2111.65  4671.5 2111.19  4759.6 2109.02  4764.9 2107.63  4784.2 2108.21
    4796 2106.34  4827.1 2104.13  4953.6 2100.26  4964.2 2099.49  4972.1 2097.17
  4977.4 2098.46  4992.7 2094.84  4993.1 2094.34    4998 2094.84  5006.6 2098.36
  5023.4 2103.08  5028.7 2103.11  5048.7 2108.51  5079.3 2113.93  5226.8 2131.48
  5240.7 2131.57  5257.4 2134.15  5272.6  2134.8  5312.3  2141.1  5318.6 2141.25
  5343.8 2148.05  5349.2 2146.66  5374.4 2154.01  5379.7 2153.63  5389.7  2155.8
#Mann= 4 ,-1 , 0
  4593.7     .16       0  4992.7     .07       0    4998     .16       0
  5312.3     .07       0
Bank Sta=4992.7,4998
XS Rating Curve= 0 ,0
Exp/Cntr=0.3,0.1

Type RM Length L Ch R = 1 ,19286   ,465,465,465
BEGIN DESCRIPTION:
45
END DESCRIPTION:
XS GIS Cut Line= 3
      1543654.99      6791487.99      1543234.95      6791087.89
        1542455.        6790288.
#Sta/Elev= 30
  4419.9 2124.05  4497.7 2117.95  4540.2 2116.76  4575.4 2113.19  4649.1  2109.4
    4717 2105.62  4915.1 2104.08  4978.7 2101.64  4985.9 2100.97  4992.8 2097.49
  4996.5 2090.57  5003.4 2090.57    5007 2085.12  5010.9 2083.37  5011.4 2082.87
  5016.9 2083.37  5021.1 2087.02  5028.1 2089.17  5077.7 2090.36  5098.8 2093.48
  5148.4 2094.91  5183.7 2100.74  5233.3 2104.47  5346.5 2105.82  5367.6 2107.82
  5374.7  2106.5  5516.2 2108.41  5721.2 2118.91    6068 2144.16  6117.2 2147.98
#Mann= 5 ,-1 , 0
  4419.9     .07       0  4649.1     .16       0  5010.9     .07       0
  5016.9     .16       0    6068     .07       0
Bank Sta=5010.9,5016.9
XS Rating Curve= 0 ,0
Exp/Cntr=0.3,0.1

Type RM Length L Ch R = 1 ,18821   ,491,491,491
BEGIN DESCRIPTION:
44
END DESCRIPTION:
XS GIS Cut Line= 3
      1543798.97      6790996.14      1543404.92      6790686.25
      1543035.07      6790628.06
#Sta/Elev= 30
  4498.7 2104.29  4521.4 2103.01  4550.3 2103.09  4556.7 2102.05  4571.1 2102.35
  4606.4 2100.49  4693.1  2098.7  4720.2 2096.36  4763.6 2094.53  4842.2 2093.88
  4877.4 2092.49  4906.3 2090.79  4912.7 2088.95  4920.8 2088.94  4927.2  2086.6
  4935.2  2086.7    4949 2084.86  4991.3 2083.61  4996.8 2079.42    5007 2079.25
  5007.5 2078.75    5013 2079.25    5018 2083.24  5030.3 2082.89  5060.7 2086.35
    5091 2086.29  5111.3 2089.75  5131.5 2091.75  5303.6 2098.03  5374.4 2102.19
#Mann= 3 ,-1 , 0
  4498.7     .16       0    5007     .07       0    5013     .16       0
Bank Sta=5007,5013
XS Rating Curve= 0 ,0
Exp/Cntr=0.3,0.1

Type RM Length L Ch R = 1 ,18330   ,477,477,477
BEGIN DESCRIPTION:
43
END DESCRIPTION:
XS GIS Cut Line= 3
      1543905.03      6790688.03       1543518.4      6790351.31
      1543104.99        6790438.
#Sta/Elev= 30
  4487.3 2090.72  4572.3 2086.95  4664.4    2085  4764.1 2086.26  4778.4 2084.16
  4792.3 2080.02  4805.9    2079  4856.2 2078.68  4870.4 2076.76  4877.1 2077.97
  4884.7 2075.87  4891.3 2076.69  4898.4 2075.76  4940.7 2076.28    4988 2073.83
  4988.5 2073.33  4994.1 2073.83  5008.4 2074.17  5013.7 2075.73  5058.3 2075.46
  5085.2 2078.88  5103.1 2084.55  5115.9 2085.76  5146.5 2085.94  5247.7 2090.21
    5310 2094.67  5320.2 2094.57  5347.5 2097.24  5402.6 2098.62  5422.4 2101.93
#Mann= 3 ,-1 , 0
  4487.3     .16       0    4988     .07       0  4994.1     .16       0
Bank Sta=4988,4994.1
XS Rating Curve= 0 ,0
Exp/Cntr=0.3,0.1

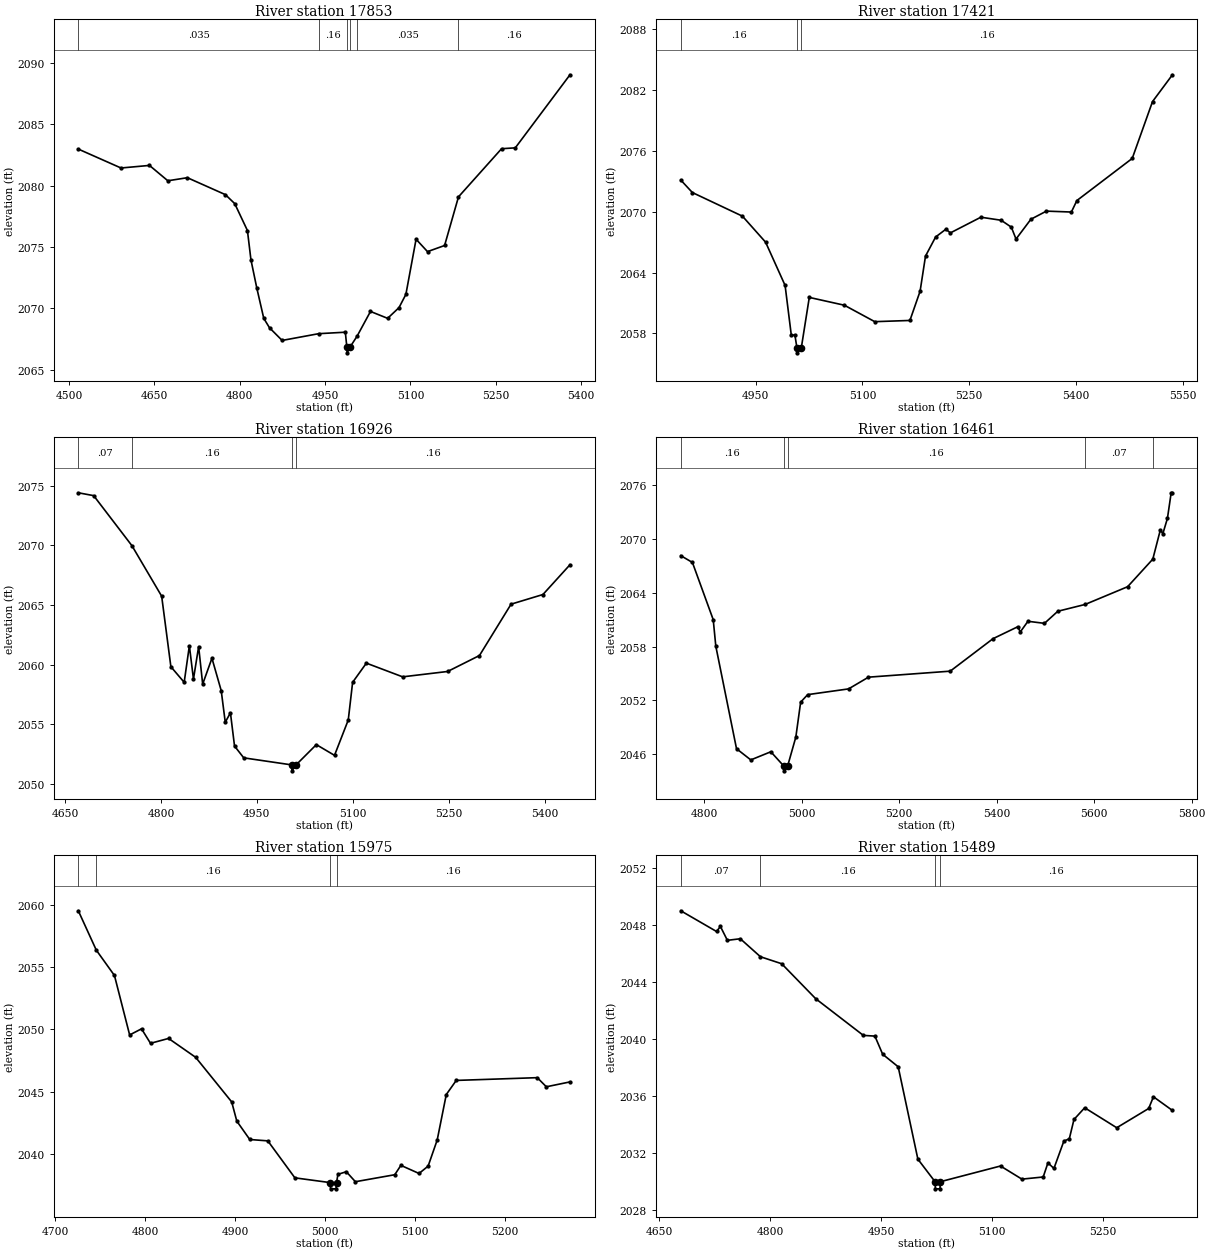
Type RM Length L Ch R = 1 ,17853   ,432,432,432
BEGIN DESCRIPTION:
42
END DESCRIPTION:
XS GIS Cut Line= 3
      1543805.01      6790338.02      1543584.79      6789907.59
        1543205.        6789888.
#Sta/Elev= 30
  4516.5 2082.97  4591.5 2081.43  4641.5 2081.64  4673.8 2080.39  4708.1 2080.64
  4774.9 2079.26  4791.3 2078.53  4813.6 2076.34  4819.8 2073.95  4830.2 2071.63
  4842.3 2069.19  4852.4 2068.42  4874.6 2067.39  4938.8 2067.94  4985.6 2068.06
  4988.2 2066.88  4988.7 2066.38  4994.3 2066.88  5006.3 2067.74  5029.8 2069.75
  5059.9 2069.19  5079.9 2070.06    5092 2071.14  5109.9 2075.63    5130 2074.62
    5160 2075.12  5184.4 2079.08  5260.1    2083  5284.2 2083.07  5380.3 2089.02
#Mann= 6 ,-1 , 0
  4516.5    .035       0  4938.8     .16       0  4988.2     .07       0
  4994.3     .16       0  5006.3    .035       0  5184.4     .16       0
Bank Sta=4988.2,4994.3
XS Rating Curve= 0 ,0
Exp/Cntr=0.3,0.1

Type RM Length L Ch R = 1 ,17421   ,495,495,495
BEGIN DESCRIPTION:
41
END DESCRIPTION:
XS GIS Cut Line= 3
      1543954.99      6789837.97      1543908.98      6789689.65
      1543504.99      6789337.99
#Sta/Elev= 30
  4844.7 2073.11    4861 2071.88  4931.4 2069.55  4963.9 2066.99  4991.3 2062.73
    5000 2057.84  5005.1 2057.84  5007.9 2056.59  5008.4 2056.09  5014.1 2056.59
  5025.3 2061.55  5074.6 2060.78  5117.3 2059.16  5166.7 2059.28    5181 2062.16
  5188.6 2065.62  5202.8  2067.5  5217.1 2068.26  5223.7 2067.91  5266.4 2069.45
  5294.9 2069.15  5309.2 2068.47  5315.8  2067.3  5336.7 2069.25  5358.5 2070.05
  5393.6 2069.96  5401.3 2071.09  5479.1 2075.24  5507.6 2080.84  5535.6 2083.48
#Mann= 3 ,-1 , 0
  4844.7     .16       0  5007.9     .07       0  5014.1     .16       0
Bank Sta=5007.9,5014.1
XS Rating Curve= 0 ,0
Exp/Cntr=0.3,0.1

Type RM Length L Ch R = 1 ,16926   ,465,465,465
BEGIN DESCRIPTION:
40
END DESCRIPTION:
XS GIS Cut Line= 3
       1544529.3      6789846.88      1544326.28      6789587.86
      1544004.98      6789287.98
#Sta/Elev= 30
  4670.9 2074.42  4694.9 2074.18  4754.7 2069.98  4801.2 2065.74  4815.6 2059.82
  4836.4 2058.51  4844.5 2061.58  4850.9 2058.78    4859 2061.51  4865.3 2058.36
  4879.8 2060.53  4894.3 2057.81  4900.6 2055.16  4908.7 2055.95  4915.1 2053.16
  4929.5 2052.17  5004.4 2051.58  5004.9 2051.08  5011.3 2051.58    5043 2053.28
  5071.4 2052.38  5092.9 2055.35  5099.7 2058.51  5121.2 2060.12  5177.9 2058.97
  5248.2 2059.42    5298 2060.76  5347.4 2065.07  5397.2 2065.88  5439.5 2068.38
#Mann= 4 ,-1 , 0
  4670.9     .07       0  4754.7     .16       0  5004.4     .07       0
  5011.3     .16       0
Bank Sta=5004.4,5011.3
XS Rating Curve= 0 ,0
Exp/Cntr=0.3,0.1

Type RM Length L Ch R = 1 ,16461   ,486,486,486
BEGIN DESCRIPTION:
39
END DESCRIPTION:
XS GIS Cut Line= 3
      1544755.01      6789588.03      1544698.94      6789346.14
      1543954.97      6789187.99
#Sta/Elev= 30
  4751.7 2068.15  4775.6 2067.39  4818.3    2061  4823.6 2058.04  4866.1 2046.59
  4895.4 2045.34  4936.5 2046.25  4963.7 2044.62  4964.2 2044.12  4970.8 2044.62
  4987.8 2047.89  4997.7 2051.79  5012.1 2052.63    5096 2053.27  5136.9 2054.58
  5304.6 2055.25  5392.5 2058.88  5443.2 2060.21  5448.4 2059.63  5464.1 2060.82
    5498 2060.59  5525.4 2061.94  5581.4  2062.7  5668.6 2064.68  5720.3 2067.76
  5735.8 2071.03  5740.9  2070.6  5750.3 2072.31    5758 2075.17  5760.6 2075.17
#Mann= 5 ,-1 , 0
  4751.7     .16       0  4963.7     .07       0  4970.8     .16       0
  5581.4     .07       0  5720.3     .16       0
Bank Sta=4963.7,4970.8
XS Rating Curve= 0 ,0
Exp/Cntr=0.3,0.1

Type RM Length L Ch R = 1 ,15975   ,486,486,486
BEGIN DESCRIPTION:
38
END DESCRIPTION:
XS GIS Cut Line= 3
        1545055.      6789338.03      1545078.28      6789064.52
      1544809.04      6789023.15
#Sta/Elev= 30
  4725.5  2059.5  4745.5 2056.35  4765.7 2054.32  4782.6 2049.56  4795.8 2050.05
  4805.8 2048.89  4825.9 2049.28    4856 2047.77  4896.1  2044.2  4901.8 2042.66
  4916.2 2041.19  4936.3 2041.08  4966.4 2038.12  5005.6 2037.74  5006.1 2037.24
  5012.2 2037.24  5012.7 2037.74  5014.3  2038.4  5023.6 2038.61  5033.7 2037.81
  5077.5 2038.37  5084.3 2039.12  5104.5 2038.47  5114.6 2039.06  5124.7 2041.15
  5134.8 2044.79  5145.9 2045.92    5236 2046.14  5246.1 2045.41  5272.4  2045.8
#Mann= 4 ,-1 , 0
  4725.5     .07       0  4745.5     .16       0  5005.6     .07       0
  5012.7     .16       0
Bank Sta=5005.6,5012.7
XS Rating Curve= 0 ,0
Exp/Cntr=0.3,0.1

Type RM Length L Ch R = 1 ,15489   ,985,985,985
BEGIN DESCRIPTION:
37
END DESCRIPTION:
XS GIS Cut Line= 3
        1545505.        6789038.      1545407.55      6788732.25
      1545193.99      6788462.96
#Sta/Elev= 30
  4679.1 2048.99  4727.4 2047.54  4732.7 2047.89  4742.1 2046.92  4759.6 2047.03
  4786.8 2045.77  4815.5 2045.28  4861.5 2042.83  4925.9 2040.26  4941.5 2040.21
    4952 2038.94    4973 2038.06  4999.6 2031.59  5022.8 2030.01  5023.3 2029.51
  5029.5 2029.51    5030 2030.01  5111.3 2031.11  5140.2 2030.19    5169 2030.34
  5175.4 2031.33  5183.5 2030.94  5196.9 2032.85  5204.3 2033.02  5210.6 2034.37
  5225.1 2035.19  5268.4 2033.79  5311.6 2035.14    5318 2035.96  5343.7    2035
#Mann= 4 ,-1 , 0
  4679.1     .07       0  4786.8     .16       0  5022.8     .07       0
    5030     .16       0
Bank Sta=5022.8,5030
XS Rating Curve= 0 ,0
Exp/Cntr=0.3,0.1

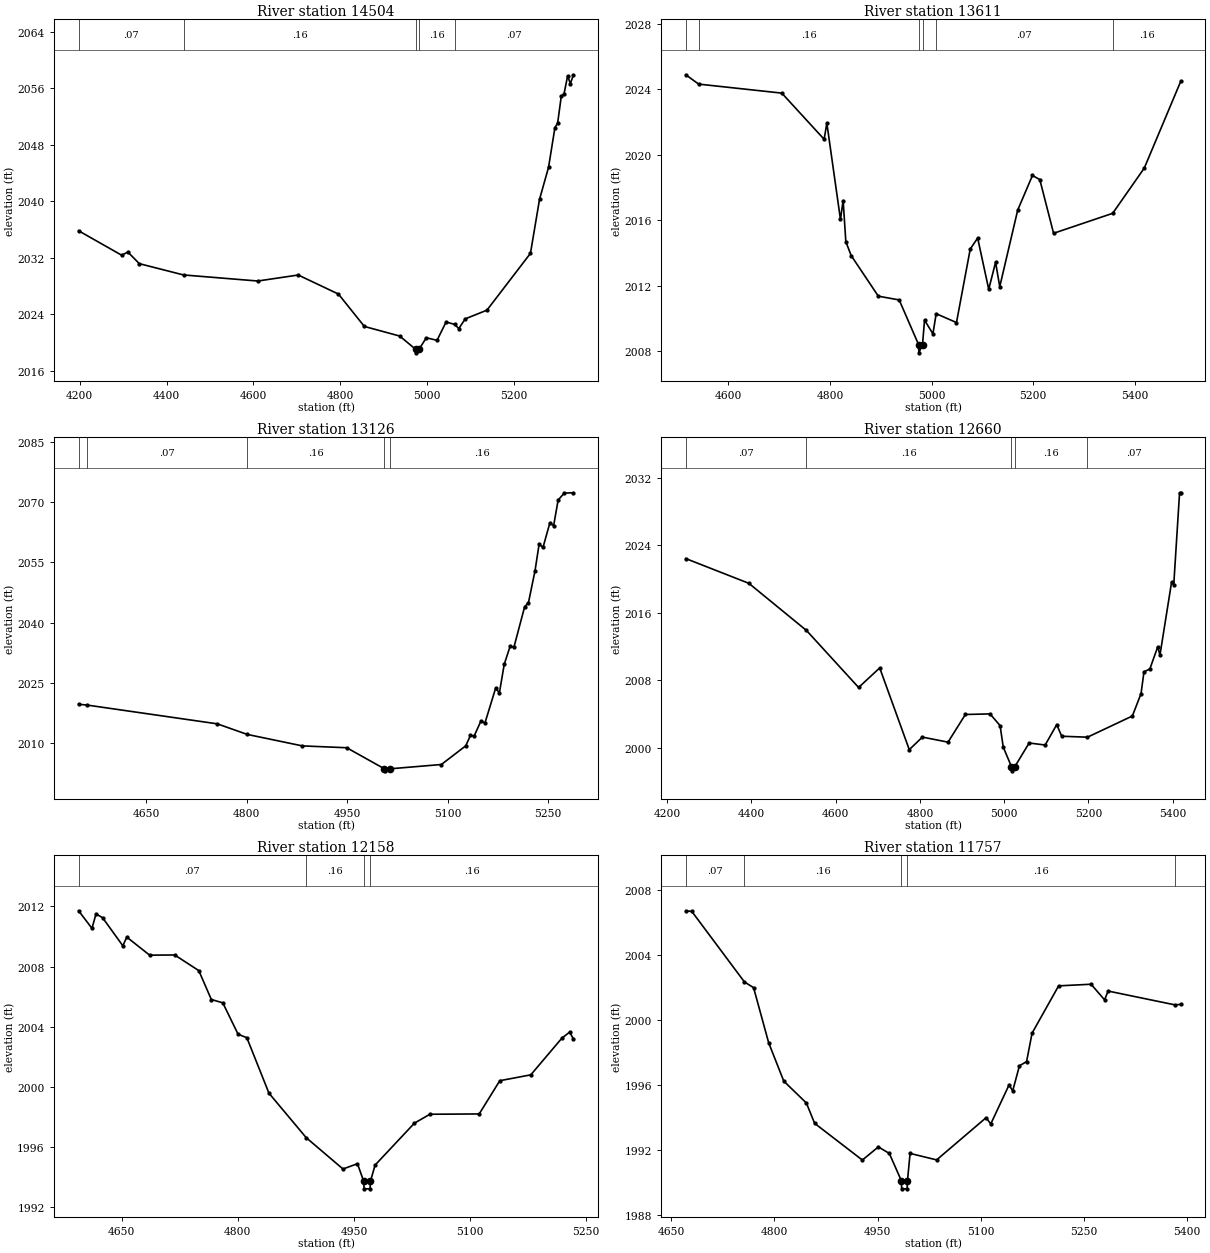
Type RM Length L Ch R = 1 ,14504   ,893,893,893
BEGIN DESCRIPTION:
36
END DESCRIPTION:
XS GIS Cut Line= 3
        1545755.      6788687.99      1545554.82      6787910.65
      1545355.02      6787638.03
#Sta/Elev= 30
  4197.3 2035.81  4296.5 2032.35  4310.9  2032.8  4337.2 2031.15  4439.1 2029.55
  4610.3 2028.69  4703.5 2029.54  4796.2 2026.84    4856 2022.25  4937.4 2020.89
  4974.2 2019.01  4974.7 2018.51  4981.9 2019.01  4998.8 2020.65  5023.5 2020.28
  5044.3 2022.88  5064.2 2022.54  5073.7 2021.94  5088.3 2023.32  5138.5 2024.56
  5238.8 2032.61  5259.7 2040.26  5280.5 2044.81  5295.2 2050.43  5301.4 2051.05
  5309.9 2054.89  5316.1 2055.17  5324.5 2057.78  5330.7 2056.66    5338 2057.92
#Mann= 5 ,-1 , 0
  4197.3     .07       0  4439.1     .16       0  4974.2     .07       0
  4981.9     .16       0  5064.2     .07       0
Bank Sta=4974.2,4981.9
XS Rating Curve= 0 ,0
Exp/Cntr=0.3,0.1

Type RM Length L Ch R = 1 ,13611   ,485,485,485
BEGIN DESCRIPTION:
35
END DESCRIPTION:
XS GIS Cut Line= 3
      1545904.99      6788188.03      1546053.44      6787727.35
      1545754.99      6787337.98
#Sta/Elev= 30
    4516 2024.88  4541.4 2024.31  4705.1 2023.76  4788.5 2020.94  4793.8 2021.93
  4820.6 2016.05  4825.9  2017.2  4831.2 2014.69  4841.7 2013.84  4895.2 2011.36
  4936.3 2011.13  4974.5  2008.4    4975  2007.9  4982.2  2008.4  4986.2  2009.9
  5002.7 2009.06  5009.1 2010.29  5049.1 2009.75  5076.2 2014.24  5090.8 2014.91
  5112.6 2011.78  5126.1 2013.43  5134.3 2011.94  5169.7 2016.62  5198.7 2018.73
  5213.2 2018.48  5240.3  2015.2  5356.7 2016.42  5418.9 2019.18  5490.6 2024.47
#Mann= 6 ,-1 , 0
    4516     .07       0  4541.4     .16       0  4974.5     .07       0
  4982.2     .16       0  5009.1     .07       0  5356.7     .16       0
Bank Sta=4974.5,4982.2
XS Rating Curve= 0 ,0
Exp/Cntr=0.3,0.1

Type RM Length L Ch R = 1 ,13126   ,466,466,466
BEGIN DESCRIPTION:
34
END DESCRIPTION:
XS GIS Cut Line= 3
      1546255.01      6787987.99      1546463.71      6787588.52
      1546604.99      6787338.01
#Sta/Elev= 30
  4549.3 2019.62  4561.2 2019.45  4756.2 2014.75  4800.7 2012.12  4883.1 2009.25
  4949.3 2008.79  5005.6 2003.53  5006.1 2003.03  5013.5 2003.53  5090.5 2004.61
  5126.9 2009.27  5133.8 2011.85  5139.5 2011.74  5149.7 2015.53  5155.4 2014.91
  5171.4 2023.61  5177.1  2022.5  5184.3 2029.62    5193 2034.05  5198.8  2033.9
  5214.7 2043.93  5220.4 2044.95  5230.2 2052.91  5236.3 2059.55  5242.1 2058.73
  5252.3 2064.83    5258 2064.19  5264.7 2070.57  5273.9 2072.29  5287.6 2072.37
#Mann= 5 ,-1 , 0
  4549.3     .16       0  4561.2     .07       0  4800.7     .16       0
  5005.6     .07       0  5013.5     .16       0
Bank Sta=5005.6,5013.5
XS Rating Curve= 0 ,0
Exp/Cntr=0.3,0.1

Type RM Length L Ch R = 1 ,12660   ,502,502,502
BEGIN DESCRIPTION:
33
END DESCRIPTION:
XS GIS Cut Line= 4
       1546741.6      6788537.35      1546779.36      6787983.78
      1546827.67      6787788.52        1546705.      6787387.98
#Sta/Elev= 30
    4244 2022.42  4393.7 2019.49  4530.5  2013.9  4654.3 2007.14  4704.4 2009.46
  4774.6 1999.77  4805.7 2001.26  4866.6 2000.66  4907.8 2003.94  4966.3 2004.01
  4990.2 2002.62  4997.7 2000.07  5017.2 1997.76  5017.7 1997.26  5025.2 1997.76
  5059.2 2000.56  5097.2 2000.32  5124.7 2002.74  5136.5 2001.36  5197.7 2001.25
  5304.2 2003.76  5324.8 2006.41  5331.8    2009  5345.7 2009.33  5364.5 2011.97
  5369.7 2010.97  5397.3 2019.62  5402.5 2019.34  5416.3 2030.22  5418.9 2030.22
#Mann= 5 ,-1 , 0
    4244     .07       0  4530.5     .16       0  5017.2     .07       0
  5025.2     .16       0  5197.7     .07       0
Bank Sta=5017.2,5025.2
XS Rating Curve= 0 ,0
Exp/Cntr=0.3,0.1

Type RM Length L Ch R = 1 ,12158   ,401,401,401
BEGIN DESCRIPTION:
32
END DESCRIPTION:
XS GIS Cut Line= 3
      1547155.01      6788287.96      1547261.05      6787896.16
        1547280.      6787663.03
#Sta/Elev= 30
  4594.1 2011.71  4611.4 2010.54  4616.6  2011.5  4625.1 2011.25  4651.3 2009.38
  4656.4 2009.96  4685.9 2008.76  4718.4 2008.77  4749.5 2007.73  4765.7 2005.81
  4780.5 2005.59  4800.3  2003.5  4811.6 2003.27  4840.2 1999.58  4888.4 1996.62
  4935.9 1994.54  4954.6 1994.89  4962.7 1993.72  4963.2 1993.22  4970.9 1993.22
  4971.4 1993.72  4977.4  1994.8  5028.3 1997.59  5048.3 1998.18    5112  1998.2
  5138.6 2000.41  5178.7  2000.8  5218.9 2003.24  5228.9 2003.64  5233.9 2003.18
#Mann= 4 ,-1 , 0
  4594.1     .07       0  4888.4     .16       0  4962.7     .07       0
  4971.4     .16       0
Bank Sta=4962.7,4971.4
XS Rating Curve= 0 ,0
Exp/Cntr=0.3,0.1

Type RM Length L Ch R = 1 ,11757   ,542,542,542
BEGIN DESCRIPTION:
31
END DESCRIPTION:
XS GIS Cut Line= 3
      1547455.02      6788187.97      1547589.91      6787887.89
      1547479.99      6787512.97
#Sta/Elev= 30
    4671 2006.73  4679.8 2006.69  4756.3 2002.35  4769.6    2002  4791.6  1998.6
  4813.5 1996.25  4846.4  1994.9  4858.4 1993.65  4927.8 1991.39    4951  1992.2
    4967  1991.8  4984.5 1990.12    4985 1989.62  4992.9 1989.62  4993.4 1990.12
  4997.2  1991.8  5035.8  1991.4  5107.8    1994  5114.5 1993.61  5141.2 1996.02
  5146.4 1995.64  5156.2 1997.19  5166.6 1997.45  5174.6  1999.2  5213.2 2002.11
  5260.4 2002.21    5280 2001.25  5285.2 2001.79  5382.4 2000.94  5390.7 2000.97
#Mann= 5 ,-1 , 0
    4671     .07       0  4756.3     .16       0  4984.5     .07       0
  4993.4     .16       0  5382.4     .07       0
Bank Sta=4984.5,4993.4
XS Rating Curve= 0 ,0
Exp/Cntr=0.3,0.1

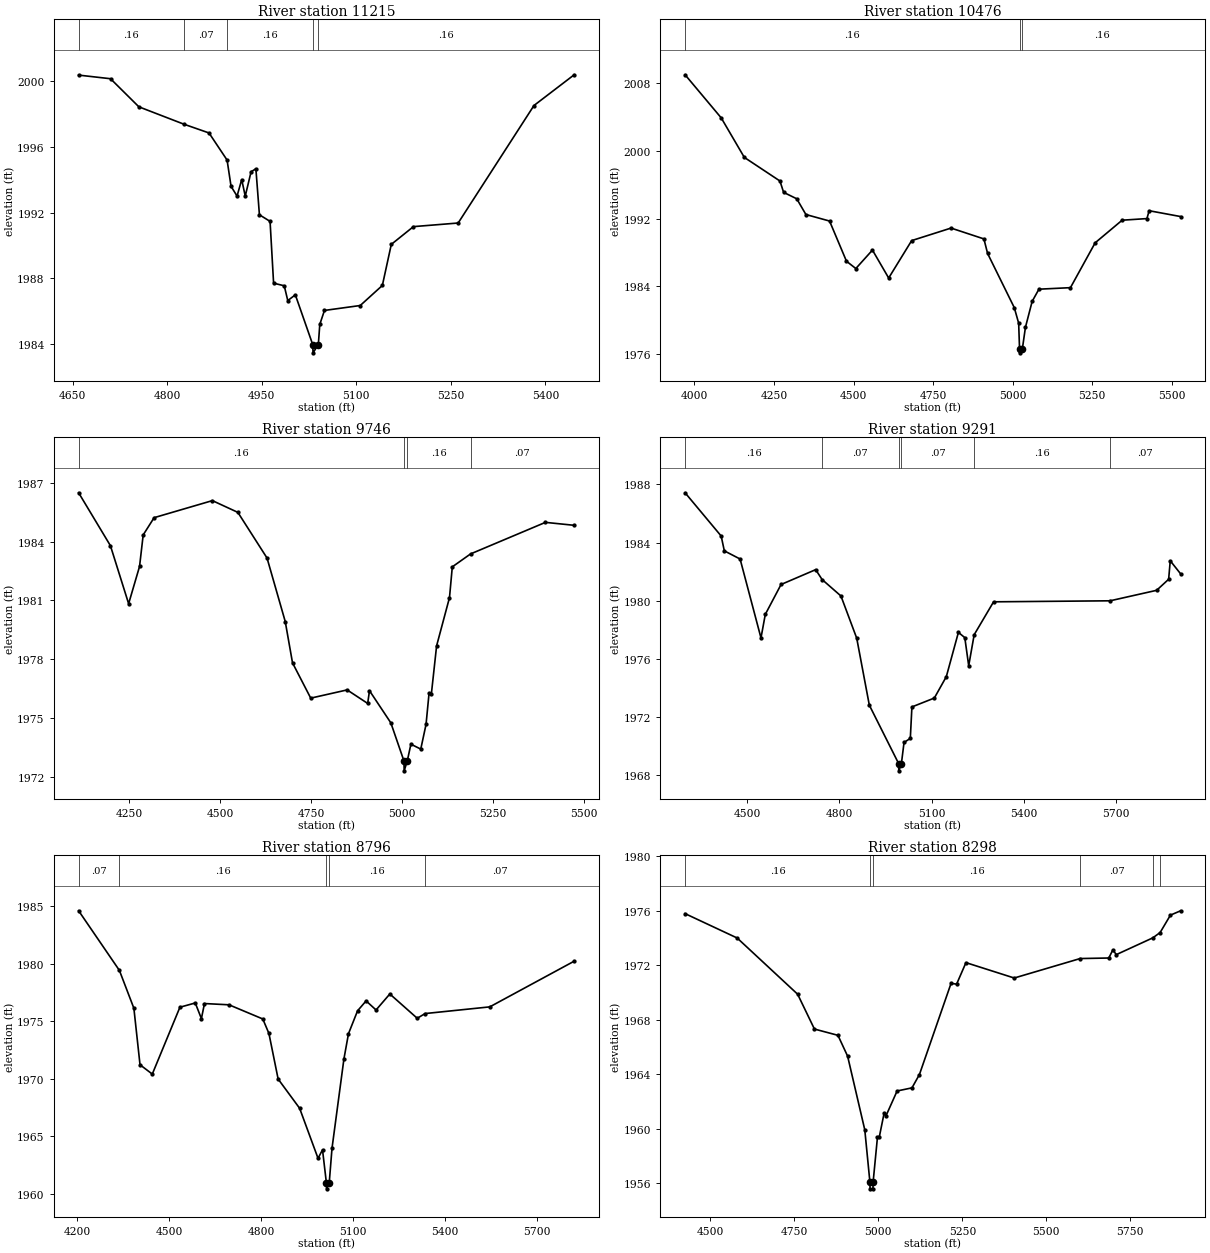
Type RM Length L Ch R = 1 ,11215   ,739,739,739
BEGIN DESCRIPTION:
30
END DESCRIPTION:
XS GIS Cut Line= 3
      1548104.48      6788273.88      1547954.85       6787967.9
      1547655.01      6787638.01
#Sta/Elev= 30
  4659.4 2000.37    4710 2000.15    4755 1998.44  4826.7 1997.38  4866.3 1996.85
    4895  1995.2  4901.3  1993.6  4910.8 1993.01  4918.2 1994.01  4923.8 1993.01
  4933.1 1994.49  4940.7 1994.67  4946.3 1991.87  4963.2 1991.47  4968.8 1987.71
  4985.7 1987.55  4991.3 1986.65  5003.3    1987  5030.9 1983.97  5031.4 1983.47
  5039.8 1983.97  5042.1  1985.2  5049.5 1986.05  5106.3 1986.35  5141.4 1987.57
  5155.6 1990.07  5190.7 1991.15  5261.7 1991.37    5382 1998.52  5445.8 2000.39
#Mann= 5 ,-1 , 0
  4659.4     .16       0  4826.7     .07       0    4895     .16       0
  5030.9     .07       0  5039.8     .16       0
Bank Sta=5030.9,5039.8
XS Rating Curve= 0 ,0
Exp/Cntr=0.3,0.1

Type RM Length L Ch R = 1 ,10476   ,730,730,730
BEGIN DESCRIPTION:
29
END DESCRIPTION:
XS GIS Cut Line= 3
        1548605.      6788537.99      1548349.58      6787540.67
      1547980.01      6787163.01
#Sta/Elev= 30
  3970.5 2009.01    4084 2003.92  4156.7 1999.25  4268.7 1996.46  4280.2 1995.12
  4321.5 1994.36  4350.3  1992.5  4424.7 1991.73  4477.9 1986.98  4507.3 1986.12
  4559.5  1988.3  4610.5    1985  4682.8 1989.42  4806.6  1990.9  4909.9 1989.62
  4921.5  1987.9  5005.4  1981.5  5019.2 1979.66  5021.9 1976.66  5022.4 1976.16
  5030.9 1976.66  5040.5 1979.18  5061.6 1982.24  5082.9 1983.68    5182 1983.86
  5259.7 1989.16  5344.5 1991.83  5422.4 1992.02  5429.4 1992.95  5528.4 1992.26
#Mann= 3 ,-1 , 0
  3970.5     .16       0  5021.9     .07       0  5030.9     .16       0
Bank Sta=5021.9,5030.9
XS Rating Curve= 0 ,0
Exp/Cntr=0.3,0.1

Type RM Length L Ch R = 1 ,9746    ,455,455,455
BEGIN DESCRIPTION:
28
END DESCRIPTION:
XS GIS Cut Line= 3
      1548729.49      6787975.32      1548718.89      6787087.48
      1548429.98      6786712.97
#Sta/Elev= 30
  4112.1 1986.49  4199.4 1983.79  4249.4 1980.83  4279.4 1982.73  4289.4 1984.34
  4319.4 1985.22  4479.4 1986.09  4549.4 1985.49  4629.5 1983.16  4679.5 1979.92
  4699.5 1977.81  4749.5 1976.01  4849.5 1976.43  4905.9 1975.74  4910.9 1976.39
  4969.5 1974.75  5005.6  1972.8  5006.1  1972.3  5014.6  1972.8  5024.6 1973.66
  5051.7 1973.41  5066.2 1974.67  5074.4 1976.25  5080.7  1976.2  5095.2 1978.68
  5130.6 1981.14  5138.3 1982.71  5188.5 1983.37  5394.1 1984.98    5473 1984.83
#Mann= 4 ,-1 , 0
  4112.1     .16       0  5005.6     .07       0  5014.6     .16       0
  5188.5     .07       0
Bank Sta=5005.6,5014.6
XS Rating Curve= 0 ,0
Exp/Cntr=0.3,0.1

Type RM Length L Ch R = 1 ,9291    ,495,495,495
BEGIN DESCRIPTION:
27
END DESCRIPTION:
XS GIS Cut Line= 3
      1548875.33      6788072.46      1549029.88       6787388.3
      1548779.99      6786512.97
#Sta/Elev= 30
  4298.6 1987.42  4415.9 1984.45  4426.2 1983.43  4477.5 1982.87  4545.4 1977.45
  4559.5 1979.07  4610.7 1981.12  4723.3 1982.14  4744.2 1981.46  4805.5 1980.33
  4856.8 1977.43  4897.8 1972.83  4993.1 1968.82  4993.6 1968.32  5002.1 1968.82
  5010.7 1970.27  5031.1 1970.55  5036.3 1972.71  5109.2 1973.32  5148.2 1974.79
  5187.5 1977.83  5208.3 1977.47    5221 1975.54  5238.8 1977.67  5301.9 1979.93
  5680.9    1980  5832.2 1980.72  5871.3 1981.48  5876.5 1982.75  5910.3 1981.85
#Mann= 6 ,-1 , 0
  4298.6     .16       0  4744.2     .07       0  4993.1     .07       0
  5002.1     .07       0  5238.8     .16       0  5680.9     .07       0
Bank Sta=4993.1,5002.1
XS Rating Curve= 0 ,0
Exp/Cntr=0.3,0.1

Type RM Length L Ch R = 1 ,8796    ,498,498,498
BEGIN DESCRIPTION:
26
END DESCRIPTION:
XS GIS Cut Line= 3
        1549405.      6787937.99      1549402.56      6787143.39
      1549030.01      6786413.02
#Sta/Elev= 30
  4205.4  1984.6  4338.2 1979.42  4385.4 1976.13  4405.4 1971.22  4445.4 1970.41
  4535.4 1976.22  4585.4 1976.59  4605.4 1975.23  4615.4 1976.54  4695.4 1976.43
  4805.4  1975.2  4825.4 1973.94  4855.4 1969.98  4925.4 1967.44  4985.4 1963.09
    5000 1963.83  5012.7 1960.94  5013.2 1960.44  5021.8 1960.94  5030.9 1963.96
  5069.7 1971.72  5084.6 1973.92  5114.2 1975.91    5142 1976.77  5174.4 1975.98
  5219.3 1977.37  5308.6 1975.26  5334.3 1975.67  5544.9 1976.25  5819.9 1980.22
#Mann= 5 ,-1 , 0
  4205.4     .07       0  4338.2     .16       0  5012.7     .07       0
  5021.8     .16       0  5334.3     .07       0
Bank Sta=5012.7,5021.8
XS Rating Curve= 0 ,0
Exp/Cntr=0.3,0.1

Type RM Length L Ch R = 1 ,8298    ,252,252,252
BEGIN DESCRIPTION:
25
END DESCRIPTION:
XS GIS Cut Line= 3
        1549880.      6787813.01       1549868.2      6787237.63
      1549454.99      6786437.98
#Sta/Elev= 30
  4424.5 1975.79  4579.5    1974  4759.6 1969.87  4809.6 1967.31  4879.6 1966.85
  4908.4 1965.32  4959.6  1959.9  4974.8 1956.07  4975.3 1955.57  4983.9 1955.57
  4984.4 1956.07  4997.3 1959.36  5002.6 1959.36  5017.2 1961.14  5022.8 1960.94
  5055.8 1962.76  5100.1 1962.99  5122.3 1963.97  5216.5 1970.67    5233 1970.61
  5260.8 1972.19  5404.6 1971.06  5600.9 1972.49  5686.2 1972.53  5698.1 1973.12
  5708.7 1972.78  5817.2 1974.01    5839  1974.4  5869.7 1975.68  5900.1    1976
#Mann= 6 ,-1 , 0
  4424.5     .16       0  4974.8     .07       0  4984.4     .16       0
  5600.9     .07       0  5817.2     .16       0    5839     .07       0
Bank Sta=4974.8,4984.4
XS Rating Curve= 0 ,0
Exp/Cntr=0.3,0.1