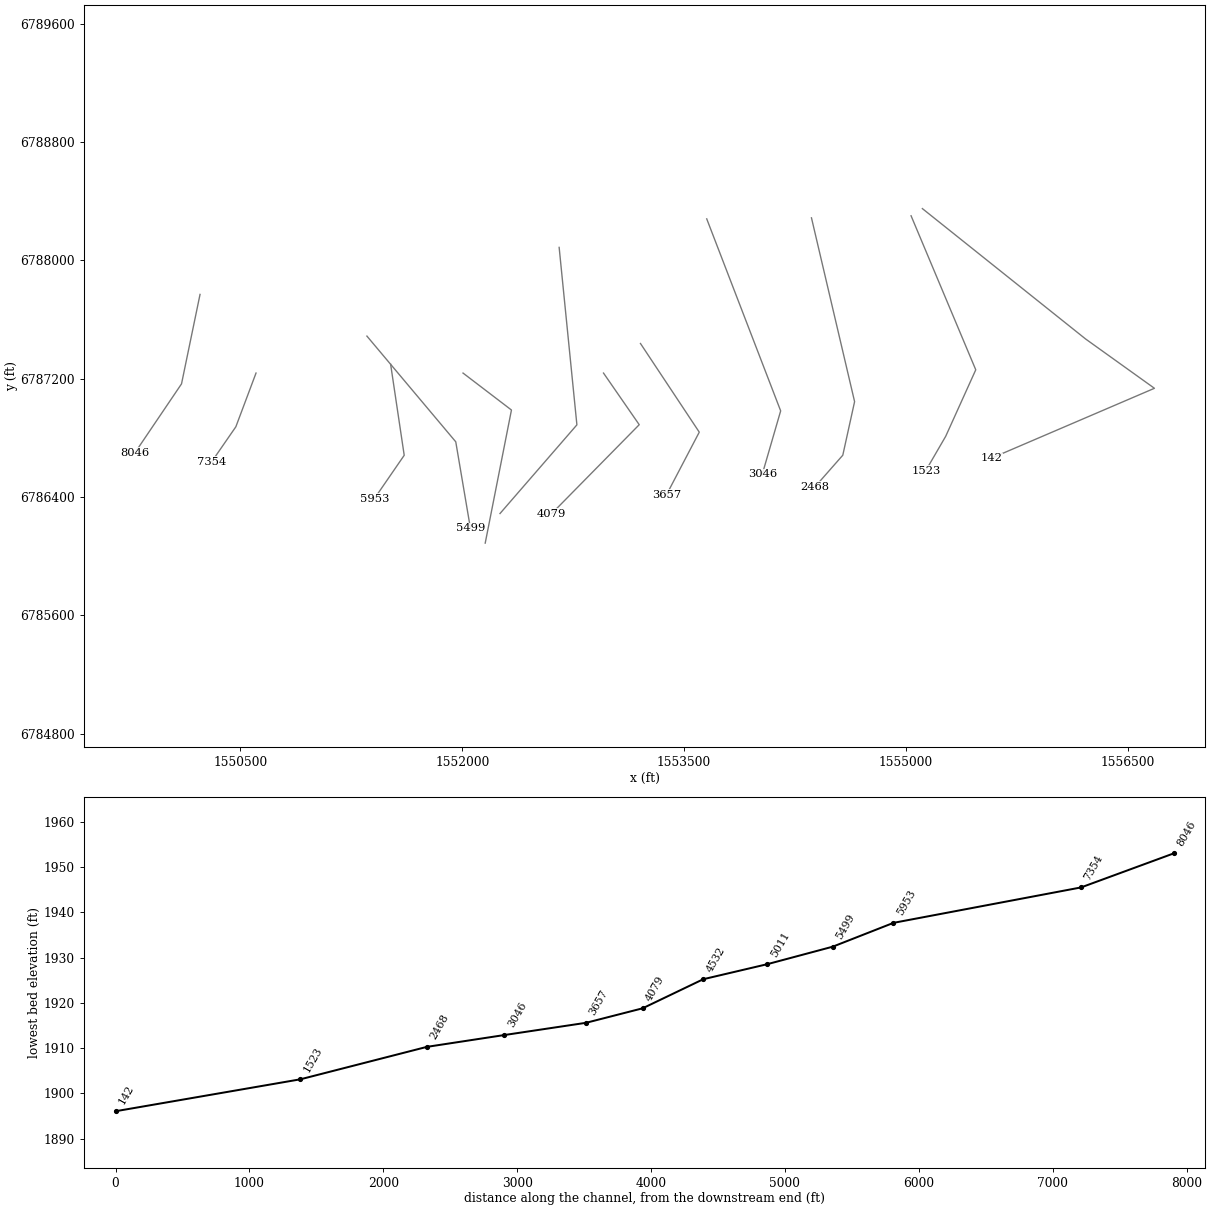
HEC-RAS study Elm 01 06.prj: Elm 01 06 Base Level Engineering

--- Elm 01 06.g01 (geometry) --- (continued)

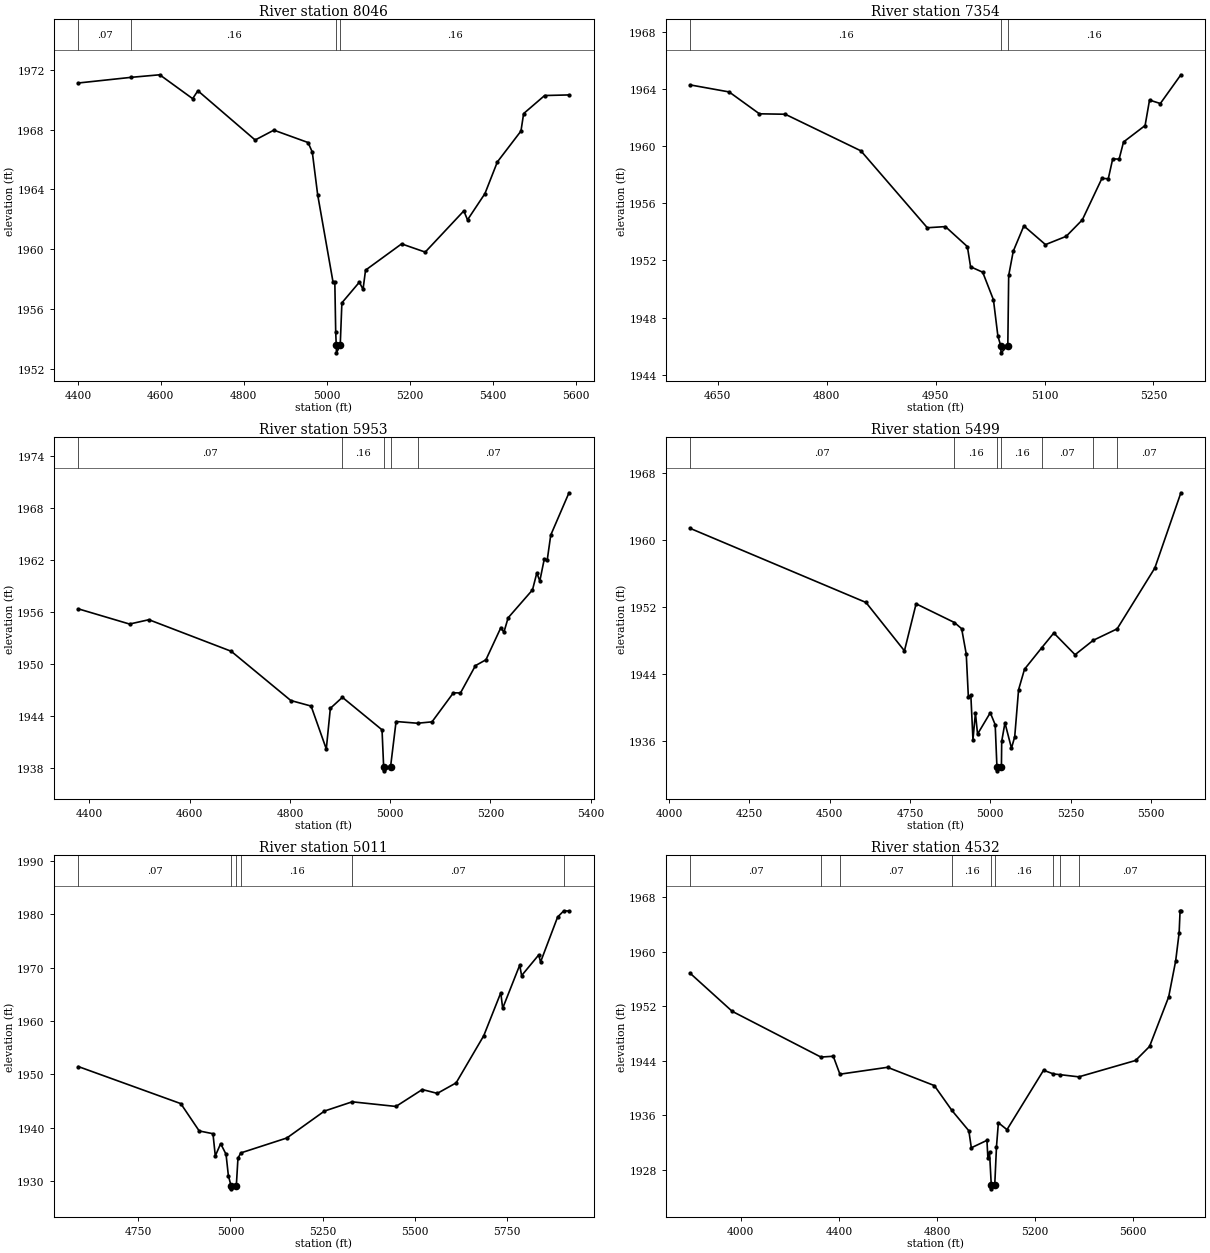
Type RM Length L Ch R = 1 ,8046    ,692,692,692
BEGIN DESCRIPTION:
24
END DESCRIPTION:
XS GIS Cut Line= 3
      1550226.36      6787769.89      1550101.12      6787164.85
      1549785.02      6786697.48
#Sta/Elev= 30
  4401.3 1971.13    4529 1971.51  4597.3 1971.68  4676.6 1970.08  4689.2 1970.61
  4827.2 1967.31  4872.3 1967.97  4954.7 1967.14  4964.9  1966.5  4977.8 1963.65
    5015 1957.77  5019.2 1957.77  5021.3 1954.45  5022.6 1953.55  5023.1 1953.05
  5032.2 1953.55  5036.2  1956.4  5078.2 1957.78  5087.2 1957.31  5093.2 1958.59
  5180.1 1960.35    5237  1959.8    5330 1962.56  5338.9 1961.96  5380.9 1963.72
  5410.8 1965.84  5467.7 1967.91  5474.1 1969.08  5524.7 1970.29  5583.4 1970.33
#Mann= 4 ,-1 , 0
  4401.3     .07       0    4529     .16       0  5022.6     .07       0
  5032.2     .16       0
Bank Sta=5022.6,5032.2
XS Rating Curve= 0 ,0
Exp/Cntr=0.3,0.1

Type RM Length L Ch R = 1 ,7354    ,1401,1401,1401
BEGIN DESCRIPTION:
23
END DESCRIPTION:
XS GIS Cut Line= 3
      1550605.02      6787238.05      1550468.64       6786874.8
      1550305.02      6786638.03
#Sta/Elev= 30
    4612 1964.27  4665.5 1963.78  4707.2 1962.25  4742.8 1962.22    4847 1959.66
  4938.5 1954.28  4963.4 1954.36  4993.7 1952.96  4998.1 1951.55  5014.8 1951.17
  5029.6 1949.24  5035.7 1946.71  5039.6 1946.03  5040.1 1945.53  5049.4 1946.03
  5050.6 1950.94  5056.9 1952.64  5071.5 1954.41  5101.3  1953.1  5129.8 1953.68
    5152 1954.83    5179 1957.73  5187.8 1957.71  5193.9  1959.1  5202.7 1959.08
  5208.8 1960.28  5238.5 1961.43  5244.6 1963.21  5259.5 1962.97  5287.8 1964.98
#Mann= 3 ,-1 , 0
    4612     .16       0  5039.6     .07       0  5049.4     .16       0
Bank Sta=5039.6,5049.4
XS Rating Curve= 0 ,0
Exp/Cntr=0.3,0.1

Type RM Length L Ch R = 1 ,5953    ,454,454,454
BEGIN DESCRIPTION:
22
END DESCRIPTION:
XS GIS Cut Line= 3
       1551515.4      6787297.17      1551607.18      6786681.88
      1551405.01      6786388.01
#Sta/Elev= 30
  4377.9 1956.38    4480 1954.63  4518.6 1955.13  4682.8 1951.49  4801.7 1945.81
  4842.2 1945.17  4872.5 1940.22  4880.6 1944.91  4904.6 1946.18  4983.7 1942.43
  4986.9  1938.2  4987.4  1937.7  5000.8  1938.2  5011.7 1943.39  5054.6 1943.19
  5083.4 1943.35  5126.1  1946.7  5140.2 1946.68    5170 1949.83    5191 1950.51
  5220.8 1954.22  5226.8 1953.68  5235.3 1955.35  5283.9 1958.57  5292.5 1960.52
  5298.5  1959.6  5307.3  1962.1  5313.4 1962.06  5320.3 1964.89  5356.7 1969.77
#Mann= 5 ,-1 , 0
  4377.9     .07       0  4904.6     .16       0  4986.9     .07       0
  5000.8     .16       0  5054.6     .07       0
Bank Sta=4986.9,5000.8
XS Rating Curve= 0 ,0
Exp/Cntr=0.3,0.1

Type RM Length L Ch R = 1 ,5499    ,488,488,488
BEGIN DESCRIPTION:
21
END DESCRIPTION:
XS GIS Cut Line= 3
      1551354.99      6787488.01      1551955.83      6786773.06
        1552055.      6786188.01
#Sta/Elev= 30
  4066.1 1961.34  4613.1 1952.51  4732.8 1946.74  4769.1 1952.35  4888.3 1950.12
  4910.9 1949.38  4925.2 1946.36  4931.8 1941.24  4939.5 1941.47  4946.1 1936.15
  4953.8 1939.33  4960.4 1936.81    5000 1939.36  5015.3 1937.93  5020.7 1932.93
  5021.2 1932.43  5034.7 1932.93  5035.6 1935.95  5045.7 1938.15    5066 1935.13
  5076.1 1936.49  5088.1  1942.1  5106.6 1944.55  5159.6 1947.08  5197.8 1948.87
    5264 1946.28  5320.3 1947.99  5394.9 1949.36  5512.3 1956.62  5593.4 1965.59
#Mann= 7 ,-1 , 0
  4066.1     .07       0  4888.3     .16       0  5020.7     .07       0
  5034.7     .16       0  5159.6     .07       0  5320.3    .035       0
  5394.9     .07       0
Bank Sta=5020.7,5034.7
XS Rating Curve= 0 ,0
Exp/Cntr=0.3,0.1

Type RM Length L Ch R = 1 ,5011    ,479,479,479
BEGIN DESCRIPTION:
20
END DESCRIPTION:
XS GIS Cut Line= 3
      1552004.97      6787238.02      1552332.46      6786988.04
      1552154.99      6786087.97
#Sta/Elev= 30
    4588 1951.48  4865.5 1944.54  4915.4 1939.42  4952.7  1938.9    4959 1934.74
  4973.5 1937.04  4988.1 1935.05  4994.4 1931.06  5001.9 1929.07  5002.4 1928.57
  5015.9 1929.07  5020.4  1934.3  5028.1  1935.3  5152.9  1938.1  5254.9 1943.15
    5330 1944.88  5448.5 1944.01  5519.9 1947.18  5560.6 1946.46  5611.6 1948.43
  5686.4 1957.26  5732.6 1965.31  5737.7 1962.41  5783.9  1970.5    5789 1968.53
  5835.3  1972.4  5840.4 1971.08  5886.6 1979.51  5903.5 1980.68  5917.4 1980.63
#Mann= 6 ,-1 , 0
    4588     .07       0  5001.9     .07       0  5015.9     .07       0
  5028.1     .16       0    5330     .07       0  5903.5    .035       0
Bank Sta=5001.9,5015.9
XS Rating Curve= 0 ,0
Exp/Cntr=0.3,0.1

Type RM Length L Ch R = 1 ,4532    ,453,453,453
BEGIN DESCRIPTION:
19
END DESCRIPTION:
XS GIS Cut Line= 3
        1552655.      6788087.99      1552775.06      6786887.78
      1552255.03      6786288.04
#Sta/Elev= 30
  3793.8 1956.83  3964.6 1951.27  4326.3 1944.56  4376.7 1944.68  4403.8 1942.05
  4597.8 1943.06  4788.7 1940.38  4860.5 1936.73  4929.4 1933.75  4939.5 1931.26
  5003.2 1932.35    5007 1929.73  5013.6 1930.67  5020.9 1925.74  5021.4 1925.24
  5034.9 1925.74  5042.1 1931.44  5049.8 1934.93  5084.9 1933.92    5234 1942.63
  5273.9 1942.09  5301.6 1941.98  5377.7 1941.66  5609.1 1944.06  5666.1 1946.12
    5744 1953.38  5772.5 1958.65  5786.7 1962.79  5790.5 1966.01  5793.8 1966.01
#Mann= 9 ,-1 , 0
  3793.8     .07       0  4326.3    .035       0  4403.8     .07       0
  4860.5     .16       0  5020.9     .07       0  5034.9     .16       0
  5273.9     .07       0  5301.6     .16       0  5377.7     .07       0
Bank Sta=5020.9,5034.9
XS Rating Curve= 0 ,0
Exp/Cntr=0.3,0.1

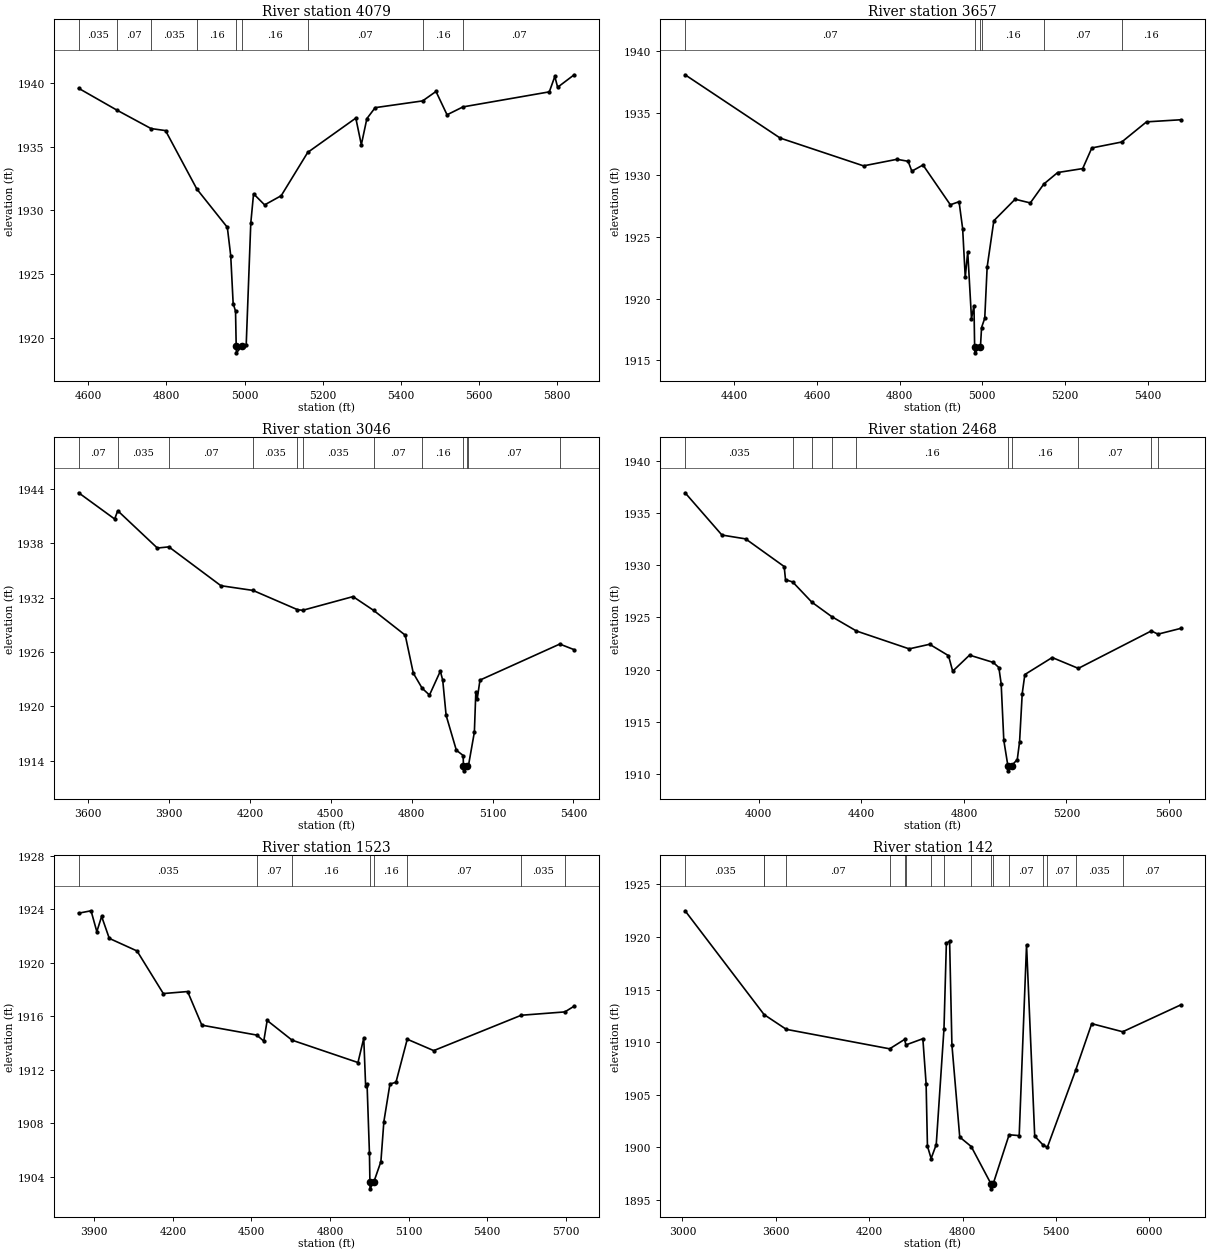
Type RM Length L Ch R = 1 ,4079    ,422,422,422
BEGIN DESCRIPTION:
18
END DESCRIPTION:
XS GIS Cut Line= 3
      1552955.02      6787237.98      1553196.57      6786888.78
      1552605.03      6786288.04
#Sta/Elev= 30
  4575.4 1939.57  4672.5 1937.87  4760.6 1936.41  4797.7 1936.25  4877.9 1931.66
  4955.8 1928.66  4964.5 1926.43  4970.7 1922.68  4976.8 1922.08  4978.5 1919.31
    4979 1918.81  4992.6 1919.31  5004.1 1919.43  5015.8 1928.99  5022.9 1931.29
  5051.2 1930.42  5093.6 1931.14  5161.5 1934.54  5284.5 1937.23  5298.6 1935.14
  5312.8 1937.19    5334 1938.05  5455.4 1938.58  5489.6 1939.32  5517.9 1937.49
  5558.7 1938.11  5779.5 1939.29  5793.6  1940.5  5800.8 1939.65  5843.1 1940.63
#Mann= 9 ,-1 , 0
  4575.4    .035       0  4672.5     .07       0  4760.6    .035       0
  4877.9     .16       0  4978.5     .07       0  4992.6     .16       0
  5161.5     .07       0  5455.4     .16       0  5558.7     .07       0
Bank Sta=4978.5,4992.6
XS Rating Curve= 0 ,0
Exp/Cntr=0.3,0.1

Type RM Length L Ch R = 1 ,3657    ,611,611,611
BEGIN DESCRIPTION:
17
END DESCRIPTION:
XS GIS Cut Line= 3
      1553205.01      6787437.99      1553602.64      6786838.35
        1553380.        6786413.
#Sta/Elev= 30
  4280.5 1938.11  4510.6 1932.99  4712.4 1930.74  4793.3 1931.27  4820.4 1931.11
  4829.4 1930.31  4856.4 1930.81  4922.6 1927.59  4943.7 1927.84  4952.4 1925.66
  4958.7 1921.72  4964.7 1923.79  4973.8 1918.38  4979.8 1919.43  4981.4 1916.11
  4981.9 1915.61  4995.5 1916.11  4998.2 1917.66  5005.9 1918.41  5011.7 1922.55
  5027.9  1926.3  5079.4 1928.04  5116.2 1927.74  5148.9 1929.27  5182.4  1930.2
    5243 1930.52  5265.1 1932.19  5337.5 1932.67  5397.5  1934.3  5480.1 1934.47
#Mann= 6 ,-1 , 0
  4280.5     .07       0  4981.4     .07       0  4995.5     .07       0
  4998.2     .16       0  5148.9     .07       0  5337.5     .16       0
Bank Sta=4981.4,4995.5
XS Rating Curve= 0 ,0
Exp/Cntr=0.3,0.1

Type RM Length L Ch R = 1 ,3046    ,578,578,578
BEGIN DESCRIPTION:
833
END DESCRIPTION:
XS GIS Cut Line= 3
      1553653.11      6788280.81       1554153.1      6786982.22
      1554028.28       6786552.3
#Sta/Elev= 30
  3563.9 1943.54  3697.6 1940.65  3709.1 1941.56  3856.1 1937.45  3898.8 1937.58
    4092  1933.3  4211.1 1932.78  4376.2 1930.66  4395.4 1930.59  4582.3  1932.1
  4658.8 1930.58  4776.1 1927.85  4806.1 1923.66  4838.9    1922  4866.1 1921.25
  4906.4 1923.89  4915.3 1922.87  4927.8 1919.02  4965.8 1915.17  4991.1 1914.59
  4992.1  1913.4  4992.6  1912.9  5006.5  1913.4  5010.6 1913.45  5032.7 1917.16
  5038.1  1921.6  5043.3 1920.84  5053.5  1922.9  5349.7 1926.87  5403.1 1926.25
#Mann= 12 ,-1 , 0
  3563.9     .07       0  3709.1    .035       0  3898.8     .07       0
  4211.1    .035       0  4376.2     .07       0  4395.4    .035       0
  4658.8     .07       0  4838.9     .16       0  4992.1     .07       0
  5006.5     .16       0  5010.6     .07       0  5349.7    .035       0
Bank Sta=4992.1,5006.5
XS Rating Curve= 0 ,0
Exp/Cntr=0.3,0.1

Type RM Length L Ch R = 1 ,2468    ,945,945,945
BEGIN DESCRIPTION:
832
END DESCRIPTION:
XS GIS Cut Line= 4
      1554361.42      6788287.82       1554653.1      6787044.72
      1554573.25      6786682.35      1554385.47      6786468.92
#Sta/Elev= 30
    3713 1936.94  3856.6 1932.89  3949.1 1932.52  4099.4 1929.87  4104.5 1928.61
  4132.6 1928.39    4207 1926.46  4284.2 1925.08  4381.3 1923.69  4586.7 1921.98
  4666.4 1922.42    4740 1921.33  4756.4 1919.84  4822.1 1921.38  4914.6 1920.68
  4936.4 1920.19  4945.4 1918.64  4955.7 1913.21  4971.5 1910.79    4972 1910.29
  4986.1 1910.79  5008.2 1911.37  5017.2 1913.08  5027.5 1917.69  5037.7 1919.52
  5144.4 1921.15  5246.3 1920.11    5531  1923.7  5556.8 1923.39  5645.2 1923.94
#Mann= 10 ,-1 , 0
    3713    .035       0  4132.6     .07       0    4207    .035       0
  4284.2     .07       0  4381.3     .16       0  4971.5     .07       0
  4986.1     .16       0  5246.3     .07       0    5531    .035       0
  5556.8     .16       0
Bank Sta=4971.5,4986.1
XS Rating Curve= 0 ,0
Exp/Cntr=0.3,0.1

Type RM Length L Ch R = 1 ,1523    ,1381,1381,1381
BEGIN DESCRIPTION:
831
END DESCRIPTION:
XS GIS Cut Line= 4
      1555035.04      6788301.68      1555472.54        6787260.
      1555269.25       6786810.3      1555134.45      6786578.02
#Sta/Elev= 30
  3840.2  1923.7  3887.6 1923.88  3909.7 1922.32    3928 1923.46  3957.2 1921.82
  4063.1 1920.88  4163.5  1917.7  4256.3 1917.85  4310.6 1915.34  4520.3  1914.6
    4547 1914.15    4560 1915.69    4655 1914.22  4906.7 1912.55  4928.8 1914.37
  4935.9 1910.81  4941.4 1910.92  4950.5 1905.77  4952.3 1903.62  4952.8 1903.12
    4967 1903.62  4994.2 1905.15  5005.5 1908.13  5028.7 1910.94  5051.8 1911.08
  5094.8 1914.29  5195.9 1913.44    5530 1916.08  5696.7 1916.33  5732.1 1916.76
#Mann= 8 ,-1 , 0
  3840.2    .035       0  4520.3     .07       0    4655     .16       0
  4952.3     .07       0    4967     .16       0  5094.8     .07       0
    5530    .035       0  5696.7     .07       0
Bank Sta=4952.3,4967
XS Rating Curve= 0 ,0
Exp/Cntr=0.3,0.1

Type RM Length L Ch R = 1 ,142     ,0,0,0
BEGIN DESCRIPTION:
16
END DESCRIPTION:
XS GIS Cut Line= 4
      1555111.46      6788350.26       1556215.6      6787468.34
      1556680.88        6787135.      1555579.98      6786662.99
#Sta/Elev= 30
    3017 1922.49  3524.6 1912.62  3667.1 1911.22    4331 1909.37  4426.7 1910.26
  4435.5 1909.74  4544.3 1910.33  4565.2 1906.06  4573.8 1900.12  4597.5 1898.94
  4630.3 1900.27  4680.1  1911.3  4695.4  1919.4  4716.2  1919.6    4731 1909.75
  4781.3 1900.98  4855.1 1900.08  4981.2 1896.56  4981.7 1896.06  4996.6 1896.56
  5098.4  1901.2  5163.2 1901.12  5210.4 1919.26  5262.9 1901.07  5317.1 1900.22
  5344.1 1900.01  5525.3 1907.31  5629.1 1911.76    5828 1910.99  6200.3 1913.54
#Mann= 17 ,-1 , 0
    3017    .035       0  3524.6     .07       0  3524.6    .035       0
  3667.1     .07       0    4331     .16       0  4426.7     .07       0
  4435.5     .16       0  4597.5     .12       0  4680.1     .07       0
  4855.1     .16       0  4981.2     .07       0  4996.6     .16       0
  5098.4     .07       0  5317.1     .16       0  5344.1     .07       0
  5525.3    .035       0    5828     .07       0
Bank Sta=4981.2,4996.6
XS Rating Curve= 0 ,0
Exp/Cntr=0.3,0.1

Chan Stop Cuts=-1
Use User Specified Reach Order=0
Composite Channel Slope=5