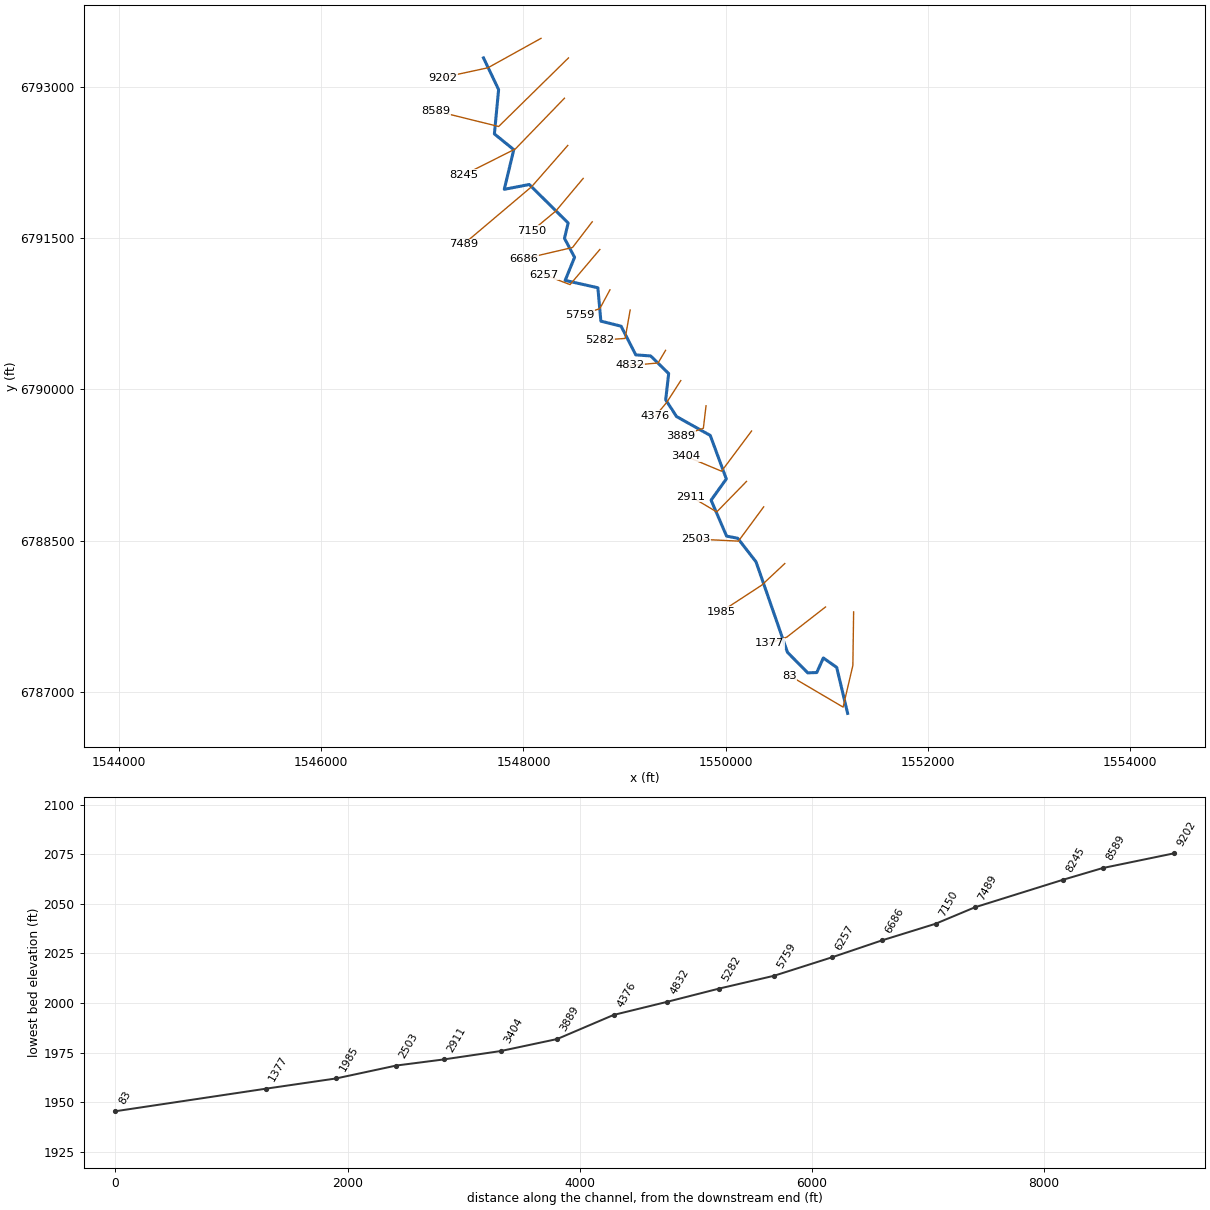
--- Elm 01 07.prj (project) ---

Proj Title=Elm 01 07 Base Level Engineering
Current Plan=p01
Default Exp/Contr=0.3,0.1
English Units
Geom File=g01
Flow File=f01
Plan File=p01
BEGIN DESCRIPTION:
Elm 01 07
END DESCRIPTION:

--- Elm 01 07.p01 (plan) ---

Plan Title=Multiple Run
Short Identifier=Multiple
Geom File=g01
Flow File=f01
Subcritical Flow
K Sum by GR= 0
Std Step Tol= 0.01
Critical Tol= 0.01
Num of Std Step Trials= 20
Max Error Tol= 0.3
Flow Tol Ratio= 0.001
Split Flow NTrial= 30
Split Flow Tol= 0.02
Split Flow Ratio= 0.02
Log Output Level= 0
Friction Slope Method= 1
Unsteady Friction Slope Method= 2
Unsteady Bridges Friction Slope Method= 1
Parabolic Critical Depth
Global Vel Dist=  1 , 1 , 1
Global Log Level= 0
CheckData=True
Encroach Param= -1, 0, 0, 0
BEGIN DESCRIPTION:
Multiple Run
END DESCRIPTION:

--- Elm 01 07.f01 (steady flow) ---

Flow Title=Multiple
Number of Profiles=7
Profile Names=10-year,25-year,50-year,1pct_min,100-year,1pct_plu,500-year
River Rch & RM= Elm 01 07,Reach-1,9202
     350     504     637     500     801    1100    1280
River Rch & RM= Elm 01 07,Reach-1,8245
     393     569     722     568     911    1250    1470
River Rch & RM= Elm 01 07,Reach-1,3404
     601     889    1140     912    1460    2010    2420
Boundary for River Rch & Prof#=Elm 01 07,Reach-1,1
Up Type=0
Dn Type=3
Dn Slope=0.005
Boundary for River Rch & Prof#=Elm 01 07,Reach-1,2
Up Type=0
Dn Type=3
Dn Slope=0.005
Boundary for River Rch & Prof#=Elm 01 07,Reach-1,3
Up Type=0
Dn Type=3
Dn Slope=0.005
Boundary for River Rch & Prof#=Elm 01 07,Reach-1,4
Up Type=0
Dn Type=3
Dn Slope=0.005
Boundary for River Rch & Prof#=Elm 01 07,Reach-1,5
Up Type=0
Dn Type=3
Dn Slope=0.005
Boundary for River Rch & Prof#=Elm 01 07,Reach-1,6
Up Type=0
Dn Type=3
Dn Slope=0.005
Boundary for River Rch & Prof#=Elm 01 07,Reach-1,7
Up Type=0
Dn Type=3
Dn Slope=0.005

--- Elm 01 07.g01 (geometry) ---

Geom Title=Existing Conditions

River Reach=Elm 01 07,Reach-1
Reach XY= 30
      1547605.00      6793288.00      1547754.33      6792974.09
      1547712.69      6792534.33      1547904.26      6792378.23
      1547810.46      6791984.97      1548057.43      6792032.60
      1548441.88      6791651.21      1548405.61      6791498.63
      1548505.30      6791310.76      1548412.34      6791081.61
      1548735.60      6791008.66      1548765.32      6790677.82
      1548965.17      6790627.67      1549110.44      6790343.19
      1549257.44      6790332.53      1549435.57      6790158.09
      1549406.20      6789897.60      1549513.15      6789731.93
      1549846.87      6789544.08      1550005.50      6789112.96
      1549855.17      6788902.12      1550008.19      6788545.72
      1550118.30      6788524.59      1550299.46      6788290.42
      1550610.22      6787393.46      1550810.57      6787190.03
      1550899.89      6787192.96      1550964.62      6787337.37
      1551096.87      6787244.08      1551205.00      6786788.00

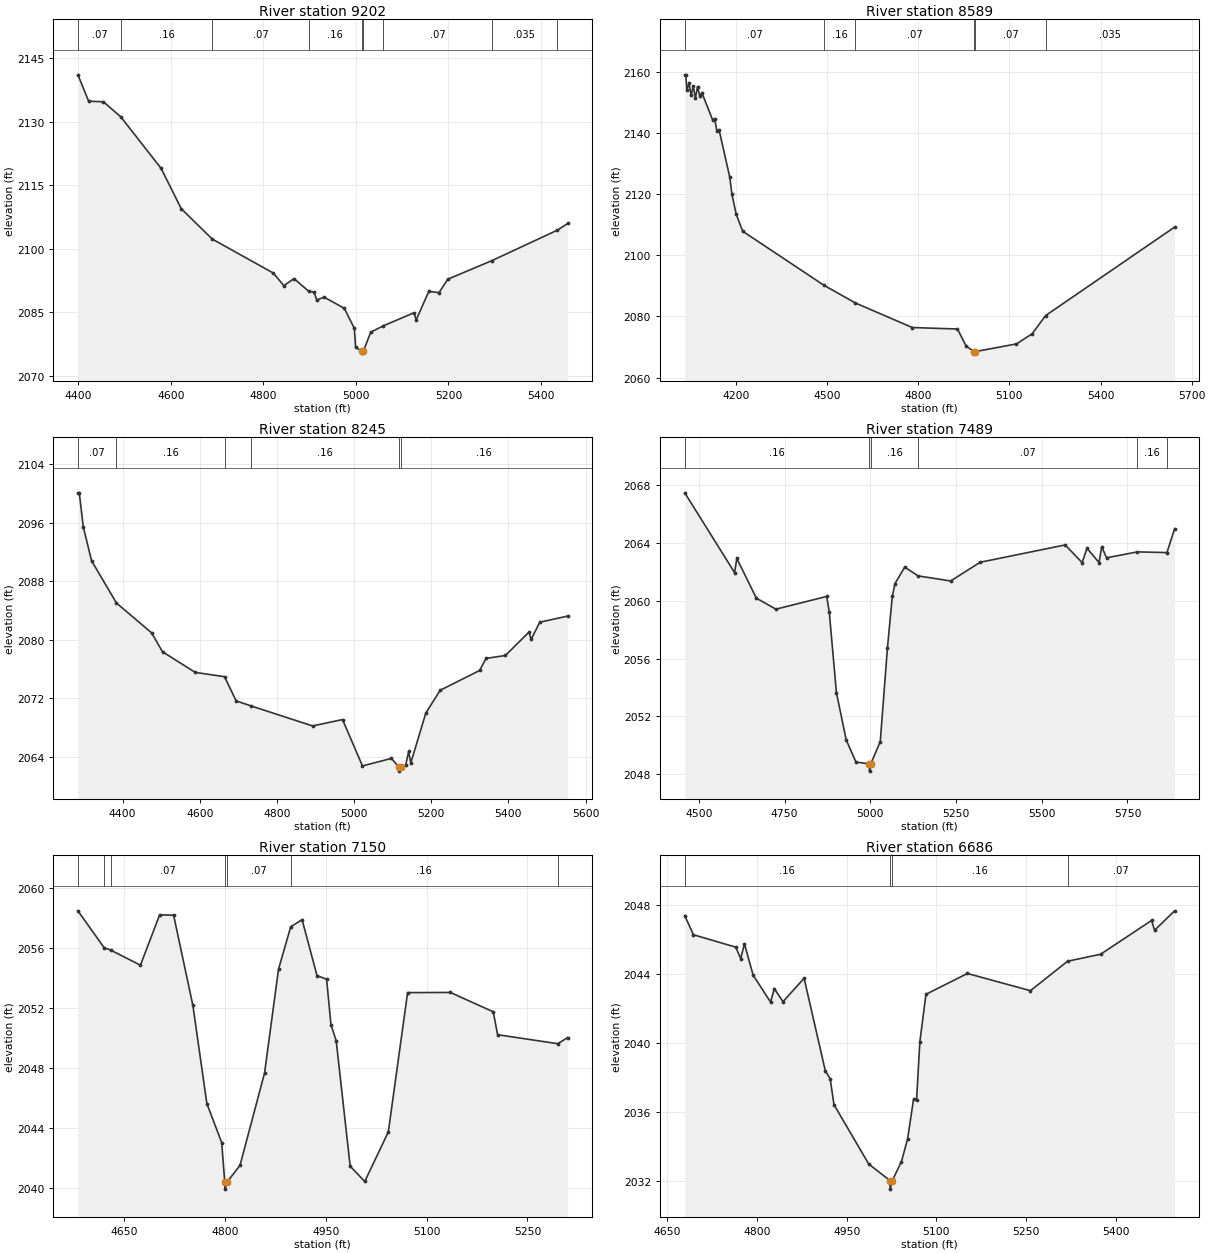
Type RM Length L Ch R = 1,9202,613,613,613
BEGIN DESCRIPTION:
197
END DESCRIPTION:
XS GIS Cut Line= 3
      1548173.91      6793482.21      1547649.05      6793190.25
      1547201.73      6793093.34
#Sta/Elev= 30
  4399.4 2141.03  4422.6 2134.81  4454.6 2134.67  4492.1 2131.11  4579.2 2118.96
  4622.7 2109.45  4689.7 2102.29  4821.5 2094.28  4844.4 2091.31  4866.3 2092.96
  4897.9 2090.00  4909.7 2089.77  4915.4 2087.94  4931.4 2088.58  4974.9 2085.97
  4996.6 2081.27  4999.5 2076.73  5012.4 2075.89  5012.6 2075.39  5016.4 2075.89
  5032.0 2080.32  5058.9 2081.81  5125.3 2084.90  5130.4 2083.26  5157.6 2089.95
  5179.6 2089.66  5198.6 2092.82  5293.1 2097.17  5434.8 2104.36  5457.7 2105.97
#Mann=9,-1,0
  4399.4    0.07       0  4492.1    0.16       0  4689.7    0.07       0
  4897.9    0.16       0  5012.4    0.07       0  5016.4    0.16       0
  5058.9    0.07       0  5293.1   0.035       0  5434.8    0.07       0
Bank Sta=5012.4,5016.4
Exp/Cntr=0.3,0.1

Type RM Length L Ch R = 1,8589,344,344,344
BEGIN DESCRIPTION:
196
END DESCRIPTION:
XS GIS Cut Line= 3
      1548444.77      6793287.79      1547754.81      6792607.98
      1547129.95      6792763.01
#Sta/Elev= 30
  4031.4 2159.14  4034.8 2159.14  4038.2 2154.11  4045.2 2156.41  4052.3 2152.55
  4059.3 2155.43  4066.4 2151.47  4073.5 2155.30  4080.6 2152.15  4087.6 2153.30
  4123.0 2144.39  4130.0 2144.83  4137.2 2140.72  4144.2 2141.18  4179.6 2125.59
  4186.6 2120.02  4200.8 2113.45  4222.0 2107.92  4489.4 2090.22  4593.2 2084.41
  4780.6 2076.37  4929.2 2075.89  4957.5 2070.31  4983.7 2068.49  4983.9 2067.99
  4987.7 2068.49  5123.4 2071.01  5175.0 2074.32  5219.0 2080.27  5643.8 2109.26
#Mann=6,-1,0
  4031.4    0.07       0  4489.4    0.16       0  4593.2    0.07       0
  4983.7    0.07       0  4987.7    0.07       0  5219.0   0.035       0
Bank Sta=4983.7,4987.7
Exp/Cntr=0.3,0.1

Type RM Length L Ch R = 1,8245,756,756,756
BEGIN DESCRIPTION:
195
END DESCRIPTION:
XS GIS Cut Line= 3
      1548405.01      6792888.01      1547920.48      6792385.78
      1547410.02      6792128.04
#Sta/Elev= 30
  4284.0 2100.09  4287.5 2100.09  4298.0 2095.43  4319.4 2090.80  4384.0 2085.02
  4475.0 2080.95  4503.3 2078.36  4588.2 2075.54  4664.1 2074.95  4694.2 2071.64
  4733.8 2070.94  4892.3 2068.22  4970.0 2069.09  5021.6 2062.75  5096.7 2063.78
  5117.0 2062.54  5117.2 2062.04  5121.0 2062.54  5133.6 2062.83  5141.3 2064.73
  5146.9 2063.15  5185.9 2069.98  5223.2 2073.10  5325.3 2075.80  5341.9 2077.45
  5392.1 2077.85  5453.4 2081.05  5459.0 2080.06  5481.3 2082.40  5553.7 2083.24
#Mann=6,-1,0
  4284.0    0.07       0  4384.0    0.16       0  4664.1    0.07       0
  4733.8    0.16       0  5117.0    0.07       0  5121.0    0.16       0
Bank Sta=5117,5121
Exp/Cntr=0.3,0.1

Type RM Length L Ch R = 1,7489,339,339,339
BEGIN DESCRIPTION:
194
END DESCRIPTION:
XS GIS Cut Line= 3
      1548437.85      6792419.76      1548081.87      6792011.85
      1547404.99      6791437.99
#Sta/Elev= 30
  4458.6 2067.45  4603.9 2061.94  4610.5 2062.92  4667.5 2060.17  4724.4 2059.41
  4872.5 2060.29  4880.1 2059.22  4901.0 2053.64  4929.5 2050.38  4957.9 2048.85
  4997.2 2048.72  4997.5 2048.22  5001.2 2048.72  5028.9 2050.26  5049.8 2056.73
  5064.0 2060.30  5071.8 2061.18  5100.3 2062.32  5139.1 2061.71  5234.3 2061.36
  5320.0 2062.65  5568.3 2063.85  5617.7 2062.63  5632.0 2063.62  5667.1 2062.63
  5674.8 2063.73  5689.1 2062.96  5779.2 2063.37  5865.1 2063.32  5887.4 2064.97
#Mann=6,-1,0
  4458.6    0.16       0  4997.2    0.07       0  5001.2    0.16       0
  5139.1    0.07       0  5779.2    0.16       0  5865.1    0.07       0
Bank Sta=4997.2,5001.2
Exp/Cntr=0.3,0.1

Type RM Length L Ch R = 1,7150,464,464,464
BEGIN DESCRIPTION:
193
END DESCRIPTION:
XS GIS Cut Line= 3
      1548590.58      6792093.31      1548321.87      6791771.43
      1548083.92      6791572.73
#Sta/Elev= 30
  4580.7 2058.50  4619.7 2056.04  4629.5 2055.88  4673.8 2054.87  4702.4 2058.23
  4723.2 2058.21  4751.9 2052.18  4772.7 2045.63  4794.8 2043.03  4799.3 2040.42
  4799.6 2039.92  4803.3 2040.42  4822.1 2041.51  4858.6 2047.67  4879.4 2054.60
  4897.6 2057.44  4914.5 2057.91  4936.7 2054.18  4951.0 2053.93  4957.5 2050.90
  4965.3 2049.82  4986.1 2041.45  5007.8 2040.43  5042.9 2043.74  5071.6 2053.04
  5135.3 2053.05  5199.1 2051.76  5205.6 2050.23  5295.2 2049.63  5310.0 2050.04
#Mann=7,-1,0
  4580.7    0.07       0  4619.7    0.16       0  4629.5    0.07       0
  4799.3    0.07       0  4803.3    0.07       0  4897.6    0.16       0
  5295.2    0.07       0
Bank Sta=4799.3,4803.3
Exp/Cntr=0.3,0.1

Type RM Length L Ch R = 1,6686,429,429,429
BEGIN DESCRIPTION:
192
END DESCRIPTION:
XS GIS Cut Line= 3
      1548680.01      6791663.02      1548485.37      6791408.14
      1548000.35      6791294.73
#Sta/Elev= 30
  4679.3 2047.39  4693.8 2046.28  4764.5 2045.56  4772.8 2044.90  4779.1 2045.75
  4793.6 2043.93  4822.7 2042.37  4829.0 2043.15  4843.5 2042.39  4878.8 2043.75
  4914.2 2038.38  4922.4 2037.91  4928.7 2036.41  4986.8 2032.96  5022.3 2032.00
  5022.6 2031.50  5026.3 2032.00  5041.5 2033.10  5051.7 2034.40  5061.7 2036.71
  5066.8 2036.67  5072.3 2040.06  5082.5 2042.82  5151.8 2044.03  5257.1 2043.03
  5319.2 2044.74  5374.6 2045.15  5459.6 2047.11  5464.7 2046.54  5498.1 2047.67
#Mann=4,-1,0
  4679.3    0.16       0  5022.3    0.07       0  5026.3    0.16       0
  5319.2    0.07       0
Bank Sta=5022.3,5026.3
Exp/Cntr=0.3,0.1

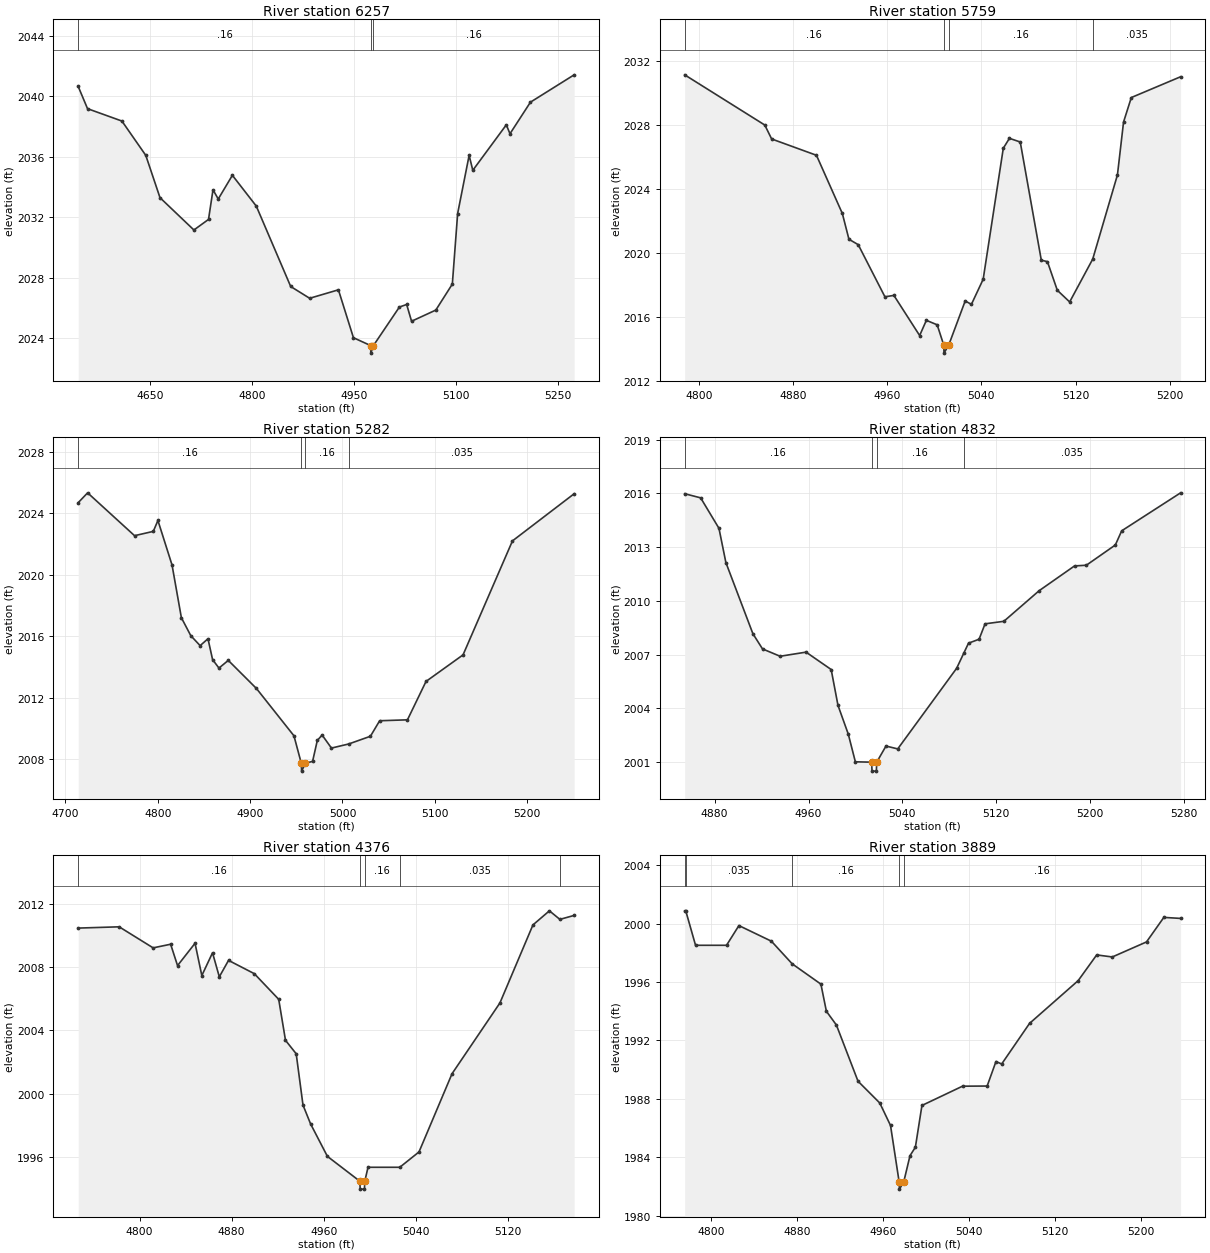
Type RM Length L Ch R = 1,6257,498,498,498
BEGIN DESCRIPTION:
191
END DESCRIPTION:
XS GIS Cut Line= 3
      1548754.98      6791387.98      1548460.62      6791039.98
      1548204.97      6791138.01
#Sta/Elev= 30
  4544.2 2040.66  4557.9 2039.19  4608.5 2038.37  4643.6 2036.10  4664.5 2033.30
  4714.4 2031.16  4735.9 2031.86  4742.5 2033.82  4750.2 2033.21  4771.0 2034.78
  4806.2 2032.74  4856.8 2027.42  4884.7 2026.64  4927.0 2027.20  4949.1 2024.03
  4974.4 2023.51  4974.7 2023.01  4978.5 2023.51  5016.7 2026.06  5027.4 2026.23
  5034.6 2025.12  5070.3 2025.86  5094.6 2027.58  5102.4 2032.25  5119.3 2036.10
  5124.7 2035.11  5174.0 2038.12  5179.4 2037.53  5209.5 2039.62  5273.8 2041.43
#Mann=3,-1,0
  4544.2    0.16       0  4974.4    0.07       0  4978.5    0.16       0
Bank Sta=4974.4,4978.5
Exp/Cntr=0.3,0.1

Type RM Length L Ch R = 1,5759,477,477,477
BEGIN DESCRIPTION:
190
END DESCRIPTION:
XS GIS Cut Line= 3
      1548854.99      6790987.98      1548754.62      6790801.02
      1548555.03      6790738.01
#Sta/Elev= 30
  4787.8 2031.12  4855.9 2027.98  4861.7 2027.11  4899.8 2026.09  4921.8 2022.45
  4927.4 2020.84  4935.3 2020.50  4958.0 2017.24  4965.6 2017.33  4987.5 2014.82
  4993.2 2015.77  5002.4 2015.49  5008.0 2014.22  5008.2 2013.72  5012.2 2014.22
  5026.2 2016.98  5031.5 2016.77  5041.5 2018.34  5058.6 2026.53  5063.8 2027.15
  5073.0 2026.92  5090.9 2019.53  5096.1 2019.44  5104.5 2017.65  5115.0 2016.92
  5134.6 2019.60  5155.6 2024.86  5160.8 2028.17  5167.4 2029.70  5209.3 2031.00
#Mann=4,-1,0
  4787.8    0.16       0  5008.0    0.07       0  5012.2    0.16       0
  5134.6   0.035       0
Bank Sta=5008,5012.2
Exp/Cntr=0.3,0.1

Type RM Length L Ch R = 1,5282,450,450,450
BEGIN DESCRIPTION:
189
END DESCRIPTION:
XS GIS Cut Line= 3
      1549055.01      6790788.04      1549005.26      6790506.30
      1548755.03      6790488.00
#Sta/Elev= 30
  4713.9 2024.69  4724.1 2025.33  4774.9 2022.54  4795.2 2022.82  4800.2 2023.53
  4815.5 2020.63  4825.6 2017.20  4835.8 2016.03  4845.9 2015.38  4854.4 2015.83
  4859.4 2014.47  4866.3 2013.92  4876.4 2014.42  4906.9 2012.59  4947.5 2009.51
  4955.5 2007.71  4955.8 2007.21  4959.8 2007.71  4967.7 2007.85  4972.8 2009.21
  4978.0 2009.56  4988.1 2008.71  5006.9 2008.98  5030.3 2009.48  5040.3 2010.49
  5070.4 2010.55  5090.5 2013.05  5130.6 2014.78  5184.1 2022.20  5250.9 2025.27
#Mann=4,-1,0
  4713.9    0.16       0  4955.5    0.07       0  4959.8    0.16       0
  5006.9   0.035       0
Bank Sta=4955.5,4959.8
Exp/Cntr=0.3,0.1

Type RM Length L Ch R = 1,4832,456,456,456
BEGIN DESCRIPTION:
188
END DESCRIPTION:
XS GIS Cut Line= 3
      1549405.00      6790388.00      1549330.88      6790262.79
      1549054.99      6790238.00
#Sta/Elev= 30
  4854.5 2015.98  4868.1 2015.75  4883.7 2014.05  4889.6 2012.14  4912.6 2008.17
  4920.8 2007.32  4935.8 2006.91  4957.9 2007.14  4979.3 2006.17  4985.1 2004.17
  4993.9 2002.56  4999.9 2001.02  5013.8 2001.00  5014.1 2000.50  5017.8 2000.50
  5018.1 2001.00  5026.0 2001.90  5036.0 2001.74  5086.2 2006.24  5092.4 2007.10
  5096.3 2007.64  5105.3 2007.86  5110.4 2008.72  5126.4 2008.86  5156.5 2010.57
  5186.6 2011.95  5196.7 2011.99  5221.4 2013.12  5226.8 2013.91  5277.0 2016.03
#Mann=4,-1,0
  4854.5    0.16       0  5013.8    0.07       0  5018.1    0.16       0
  5092.4   0.035       0
Bank Sta=5013.8,5018.1
Exp/Cntr=0.3,0.1

Type RM Length L Ch R = 1,4376,487,487,487
BEGIN DESCRIPTION:
187
END DESCRIPTION:
XS GIS Cut Line= 3
      1549555.00      6790088.00      1549418.39      6789874.69
      1549305.00      6789738.00
#Sta/Elev= 30
  4746.7 2010.46  4782.3 2010.54  4811.8 2009.21  4827.0 2009.44  4833.0 2008.09
  4848.2 2009.50  4854.1 2007.46  4863.4 2008.90  4869.3 2007.38  4877.3 2008.42
  4899.7 2007.58  4920.9 2005.96  4926.8 2003.37  4936.1 2002.52  4942.0 1999.28
  4948.6 1998.09  4963.2 1996.04  4991.4 1994.47  4991.7 1993.97  4995.4 1993.97
  4995.7 1994.47  4998.5 1995.35  5026.1 1995.35  5042.8 1996.32  5071.5 2001.26
  5113.1 2005.73  5141.8 2010.66  5156.1 2011.55  5165.2 2011.01  5177.6 2011.26
#Mann=5,-1,0
  4746.7    0.16       0  4991.4    0.07       0  4995.7    0.16       0
  5026.1   0.035       0  5165.2    0.07       0
Bank Sta=4991.4,4995.7
Exp/Cntr=0.3,0.1

Type RM Length L Ch R = 1,3889,485,485,485
BEGIN DESCRIPTION:
186
END DESCRIPTION:
XS GIS Cut Line= 3
      1549805.00      6789838.00      1549778.58      6789615.16
      1549555.02      6789538.01
#Sta/Elev= 30
  4775.6 2000.87  4776.6 2000.87  4785.7 1998.51  4814.5 1998.51  4826.0 1999.86
  4856.2 1998.79  4875.5 1997.24  4902.2 1995.85  4907.3 1993.99  4916.6 1993.05
  4936.7 1989.20  4956.9 1987.71  4966.9 1986.17  4974.9 1982.31  4975.2 1981.81
  4979.2 1982.31  4985.0 1984.10  4990.0 1984.68  4996.1 1987.54  5033.8 1988.86
  5056.7 1988.87  5064.9 1990.55  5070.2 1990.38  5096.1 1993.16  5141.3 1996.09
  5158.5 1997.85  5173.0 1997.71  5204.8 1998.74  5220.9 2000.42  5236.5 2000.35
#Mann=5,-1,0
  4775.6    0.07       0  4776.6   0.035       0  4875.5    0.16       0
  4974.9    0.07       0  4979.2    0.16       0
Bank Sta=4974.9,4979.2
Exp/Cntr=0.3,0.1

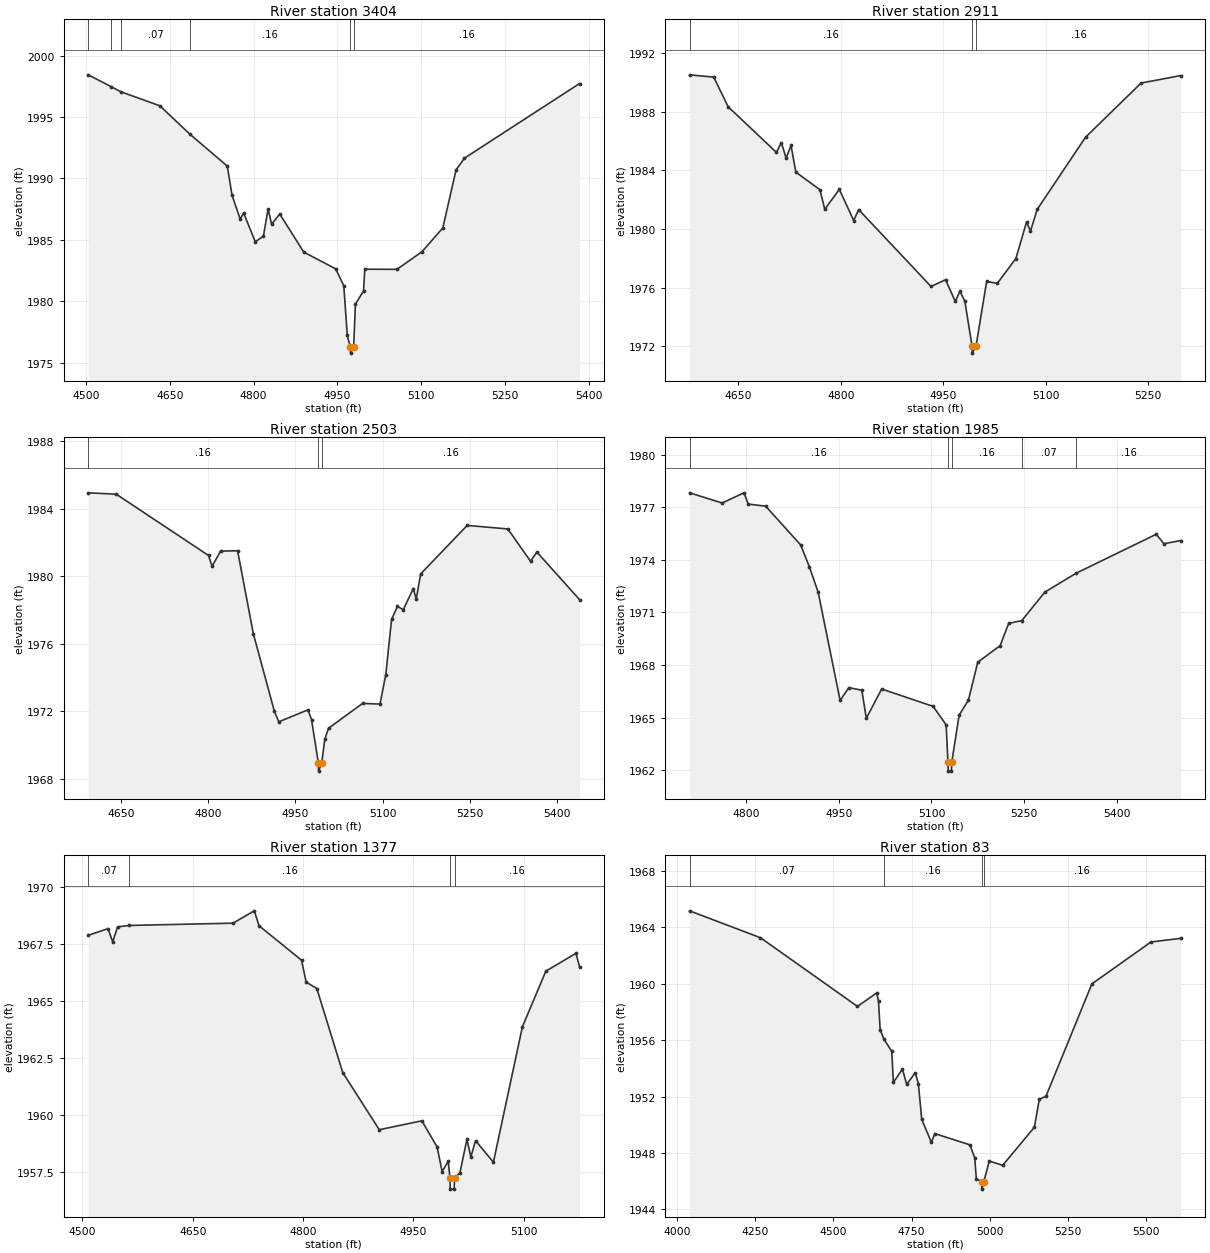
Type RM Length L Ch R = 1,3404,493,493,493
BEGIN DESCRIPTION:
185
END DESCRIPTION:
XS GIS Cut Line= 3
      1550255.00      6789588.00      1549958.89      6789189.58
      1549604.95      6789338.02
#Sta/Elev= 30
  4503.6 1998.43  4545.0 1997.46  4562.1 1997.05  4631.9 1995.91  4685.5 1993.61
  4752.8 1991.00  4761.2 1988.64  4775.8 1986.69  4782.1 1987.18  4802.9 1984.84
  4817.5 1985.30  4825.9 1987.52  4832.1 1986.27  4846.7 1987.10  4889.8 1984.00
  4946.9 1982.64  4961.5 1981.26  4967.7 1977.22  4973.1 1976.28  4973.6 1975.78
  4979.1 1976.28  4982.3 1979.76  4996.9 1980.85  4999.1 1982.61  5056.8 1982.60
  5101.8 1984.04  5138.9 1985.97  5162.7 1990.70  5177.7 1991.65  5383.8 1997.72
#Mann=6,-1,0
  4503.6    0.07       0  4545.0    0.16       0  4562.1    0.07       0
  4685.5    0.16       0  4973.1    0.07       0  4979.1    0.16       0
Bank Sta=4973.1,4979.1
Exp/Cntr=0.3,0.1

Type RM Length L Ch R = 1,2911,408,408,408
BEGIN DESCRIPTION:
184
END DESCRIPTION:
XS GIS Cut Line= 3
      1550205.03      6789088.03      1549911.08      6788785.80
      1549654.99      6788938.01
#Sta/Elev= 30
  4578.4 1990.53  4613.8 1990.37  4634.9 1988.35  4705.7 1985.23  4712.8 1985.90
  4719.8 1984.85  4727.0 1985.71  4734.0 1983.89  4769.4 1982.68  4776.4 1981.35
  4797.7 1982.71  4818.8 1980.58  4826.0 1981.33  4932.0 1976.08  4953.3 1976.54
  4967.5 1975.06  4974.4 1975.76  4981.6 1975.07  4992.0 1972.03  4992.5 1971.53
  4998.0 1972.03  5013.5 1976.43  5029.1 1976.29  5056.3 1977.99  5071.9 1980.48
  5077.7 1979.87  5087.5 1981.34  5158.3 1986.27  5239.7 1989.97  5297.9 1990.48
#Mann=3,-1,0
  4578.4    0.16       0  4992.0    0.07       0  4998.0    0.16       0
Bank Sta=4992,4998
Exp/Cntr=0.3,0.1

Type RM Length L Ch R = 1,2503,518,518,518
BEGIN DESCRIPTION:
836
END DESCRIPTION:
XS GIS Cut Line= 3
      1550375.30      6788836.36      1550125.32      6788496.11
      1549701.73      6788516.95
#Sta/Elev= 30
  4593.0 1984.94  4641.3 1984.86  4800.2 1981.23  4806.4 1980.59  4821.0 1981.49
  4850.3 1981.51  4877.4 1976.60  4913.6 1972.01  4921.3 1971.38  4971.5 1972.09
  4977.7 1971.51  4989.3 1968.96  4989.8 1968.46  4995.3 1968.96  5000.5 1970.35
  5007.0 1971.00  5065.6 1972.47  5095.6 1972.43  5105.6 1974.18  5115.6 1977.45
  5125.7 1978.21  5135.7 1978.02  5153.0 1979.27  5158.0 1978.64  5165.7 1980.14
  5245.8 1983.01  5315.9 1982.80  5354.9 1980.89  5365.9 1981.43  5439.3 1978.62
#Mann=3,-1,0
  4593.0    0.16       0  4989.3    0.07       0  4995.3    0.16       0
Bank Sta=4989.3,4995.3
Exp/Cntr=0.3,0.1

Type RM Length L Ch R = 1,1985,608,608,608
BEGIN DESCRIPTION:
835
END DESCRIPTION:
XS GIS Cut Line= 3
      1550583.65      6788273.88      1550354.49      6788058.61
      1549951.74      6787794.75
#Sta/Elev= 30
  4708.1 1977.82  4761.0 1977.24  4796.2 1977.82  4803.1 1977.18  4831.4 1977.06
  4888.1 1974.85  4902.2 1973.60  4916.4 1972.16  4952.0 1965.99  4966.2 1966.72
  4987.2 1966.57  4994.4 1964.97  5019.3 1966.64  5102.7 1965.65  5123.8 1964.60
  5126.7 1962.46  5127.2 1961.96  5132.3 1961.96  5132.8 1962.46  5144.8 1965.15
  5159.9 1966.01  5175.0 1968.17  5211.2 1969.11  5225.1 1970.38  5246.4 1970.54
  5283.6 1972.16  5334.4 1973.24  5464.2 1975.46  5476.4 1974.92  5504.0 1975.10
#Mann=5,-1,0
  4708.1    0.16       0  5126.7    0.07       0  5132.8    0.16       0
  5246.4    0.07       0  5334.4    0.16       0
Bank Sta=5126.7,5132.8
Exp/Cntr=0.3,0.1

Type RM Length L Ch R = 1,1377,1294,1294,1294
BEGIN DESCRIPTION:
834
END DESCRIPTION:
XS GIS Cut Line= 3
      1550986.41      6787843.32      1550604.49      6787544.72
      1550431.92      6787482.60
#Sta/Elev= 30
  4507.9 1967.88  4534.8 1968.17  4541.2 1967.59  4547.8 1968.25  4563.9 1968.31
  4704.8 1968.41  4733.8 1968.95  4740.1 1968.30  4798.0 1966.79  4804.3 1965.83
  4818.8 1965.55  4854.1 1961.87  4903.8 1959.37  4961.7 1959.76  4982.5 1958.61
  4989.2 1957.54  4997.6 1957.99  4999.8 1957.27  5000.3 1956.77  5005.6 1956.77
  5006.1 1957.27  5013.4 1957.48  5023.0 1958.95  5028.3 1958.18  5034.7 1958.89
  5059.0 1957.95  5098.4 1963.87  5130.3 1966.31  5171.2 1967.09  5176.1 1966.51
#Mann=4,-1,0
  4507.9    0.07       0  4563.9    0.16       0  4999.8    0.07       0
  5006.1    0.16       0
Bank Sta=4999.8,5006.1
Exp/Cntr=0.3,0.1

Type RM Length L Ch R = 1,83,0,0,0
BEGIN DESCRIPTION:
183
END DESCRIPTION:
XS GIS Cut Line= 4
      1551264.21      6787794.77      1551256.69      6787263.39
      1551160.04      6786850.28      1550630.01      6787162.99
#Sta/Elev= 30
  4039.8 1965.17  4266.6 1963.26  4576.8 1958.39  4638.4 1959.35  4644.0 1958.74
  4649.2 1956.75  4661.1 1956.07  4686.5 1955.20  4691.6 1953.00  4720.5 1953.94
  4734.1 1952.86  4761.6 1953.68  4771.5 1952.92  4782.2 1950.38  4813.0 1948.75
  4824.2 1949.37  4936.2 1948.57  4951.7 1947.66  4956.8 1946.17  4974.2 1945.93
  4974.7 1945.43  4980.5 1945.93  4998.2 1947.42  5041.1 1947.12  5142.5 1949.82
  5158.2 1951.80  5179.6 1952.02  5326.5 1959.99  5515.3 1962.96  5610.9 1963.22
#Mann=4,-1,0
  4039.8    0.07       0  4661.1    0.16       0  4974.2    0.07       0
  4980.5    0.16       0
Bank Sta=4974.2,4980.5
Exp/Cntr=0.3,0.1

Chan Stop Cuts=-1