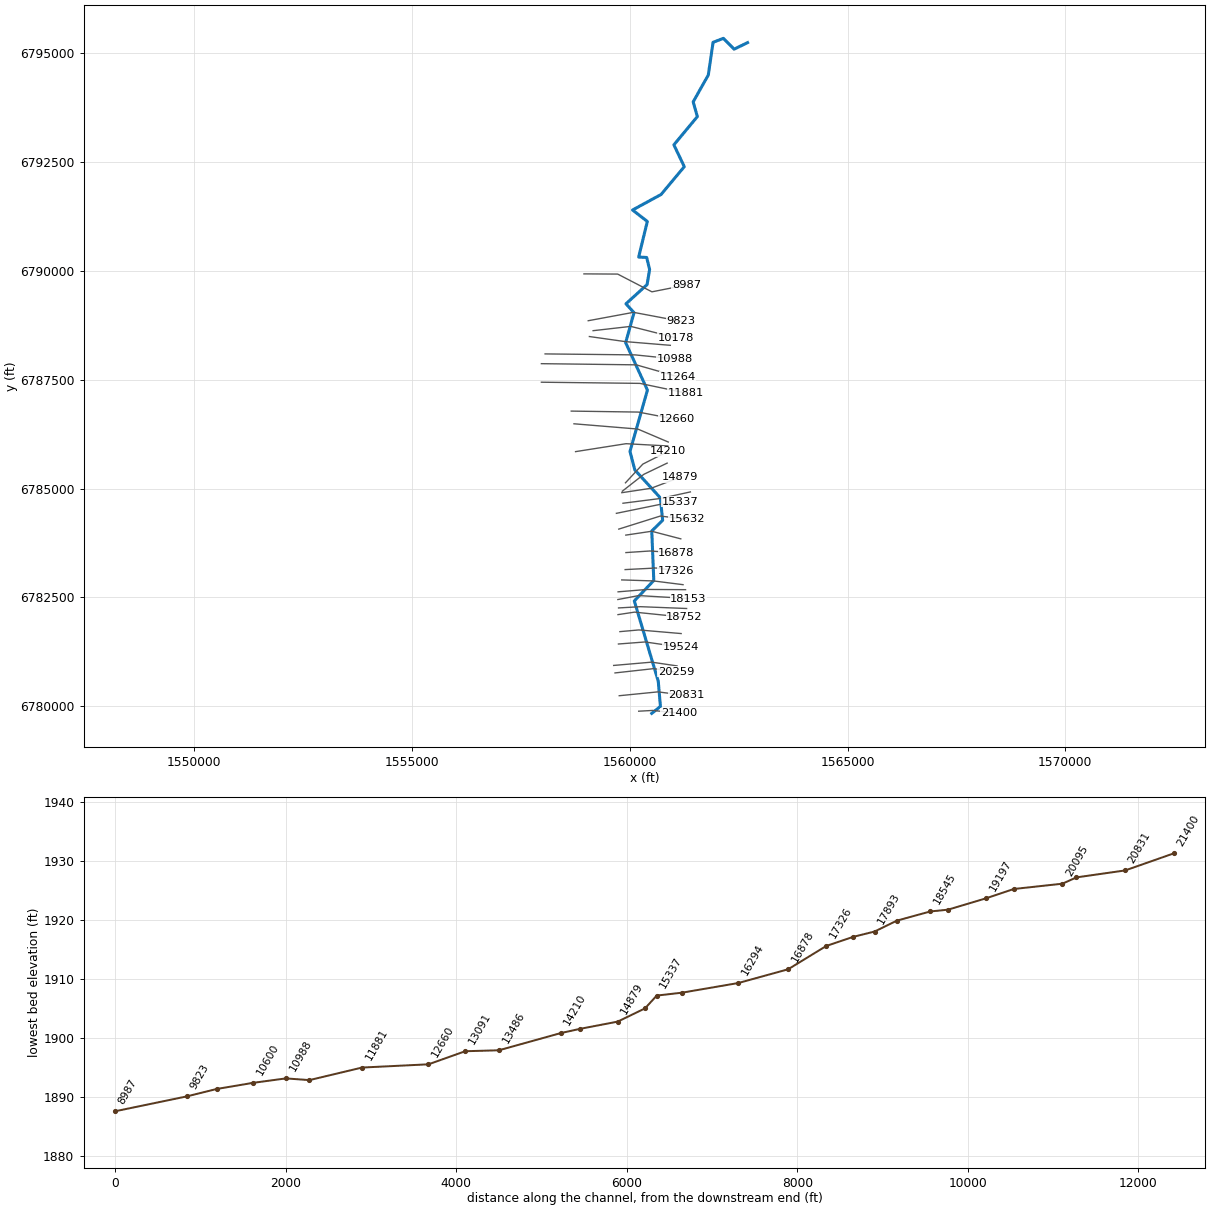
--- Elm 01 08.prj (project) ---

Proj Title=Elm 01 08 Base Level Engineering
Current Plan=p01
Default Exp/Contr=0.3,0.1
English Units
Geom File=g01
Flow File=f01
Plan File=p01
Y Axis Title=Elevation
X Axis Title(PF)=Main Channel Distance
X Axis Title(XS)=Station
BEGIN DESCRIPTION:
Elm 01 08
END DESCRIPTION:
DSS Export Rating Curves= 0
DSS Export Rating Curve Sorted= 0
DSS Export Volume Flow Curves= 0
DXF OffsetX= 0
DXF OffsetY= 0
DXF ScaleX= 1
DXF ScaleY= 10

--- Elm 01 08.p01 (plan) ---

Plan Title=Multiple Run
Short Identifier=Multiple
Geom File=g01
Flow File=f01
Subcritical Flow
K Sum by GR= 0
Std Step Tol= 0.01
Critical Tol= 0.01
Num of Std Step Trials= 20
Max Error Tol= 0.3
Flow Tol Ratio= 0.001
Split Flow NTrial= 30
Split Flow Tol= 0.02
Split Flow Ratio= 0.02
Log Output Level= 0
Friction Slope Method= 1
Unsteady Friction Slope Method= 2
Unsteady Bridges Friction Slope Method= 1
Parabolic Critical Depth
Global Vel Dist=  1 , 1 , 1
Global Log Level= 0
CheckData=True
Encroach Param= -1, 0, 0, 0
BEGIN DESCRIPTION:
Multiple Run
END DESCRIPTION:

--- Elm 01 08.f01 (steady flow) ---

Flow Title=Multiple
Number of Profiles=7
Profile Names=10-year,25-year,50-year,1pct_min,100-year,1pct_plu,500-year
River Rch & RM= Elm 01 08,Reach-1,21400
     248     344     423     324     518     713     787
River Rch & RM= Elm 01 08,Reach-1,20831
     375     531     662     512     821    1130    1280
River Rch & RM= Elm 01 08,Reach-1,17326
     454     650     816     634    1020    1400    1600
River Rch & RM= Elm 01 08,Reach-1,13486
     655     950    1200     943    1510    2080    2420
River Rch & RM= Elm 01 08,Reach-1,9823
     767    1120    1410    1110    1780    2440    2840
River Rch & RM= Elm 01 08,Reach-1,3387
     808    1170    1490    1160    1870    2570    2980
Boundary for River Rch & Prof#=Elm 01 08,Reach-1,1
Up Type=0
Dn Type=3
Dn Slope=0.005
Boundary for River Rch & Prof#=Elm 01 08,Reach-1,2
Up Type=0
Dn Type=3
Dn Slope=0.005
Boundary for River Rch & Prof#=Elm 01 08,Reach-1,3
Up Type=0
Dn Type=3
Dn Slope=0.005
Boundary for River Rch & Prof#=Elm 01 08,Reach-1,4
Up Type=0
Dn Type=3
Dn Slope=0.005
Boundary for River Rch & Prof#=Elm 01 08,Reach-1,5
Up Type=0
Dn Type=3
Dn Slope=0.005
Boundary for River Rch & Prof#=Elm 01 08,Reach-1,6
Up Type=0
Dn Type=3
Dn Slope=0.005
Boundary for River Rch & Prof#=Elm 01 08,Reach-1,7
Up Type=0
Dn Type=3
Dn Slope=0.005

--- Elm 01 08.g01 (geometry) ---

Geom Title=Existing Conditions
Program Version=4.10

River Reach=Elm 01 08       ,Reach-1
Reach XY= 30
        1560505.        6779838.      1560703.98      6779997.46
      1560654.46      6780574.14      1560104.57      6782419.63
      1560551.46      6782889.46      1560505.35      6784024.25
      1560754.95      6784272.29      1560701.47      6784786.53
       1560116.1      6785427.89      1560005.33      6785851.91
       1560405.6       6787260.7       1559905.7       6788348.7
      1560097.95      6789038.07      1559912.59      6789241.33
       1560397.2      6789681.79       1560455.5      6790027.83
       1560388.7       6790305.3      1560204.55      6790314.57
      1560402.96      6791132.15      1560063.95      6791394.67
      1560718.73       6791751.2      1561251.99      6792389.43
      1561012.79      6792891.04      1561551.56      6793539.26
      1561455.97      6793877.71      1561802.83      6794493.44
      1561912.73       6795244.5      1562149.56      6795336.34
      1562395.84      6795087.17        1562705.        6795238.

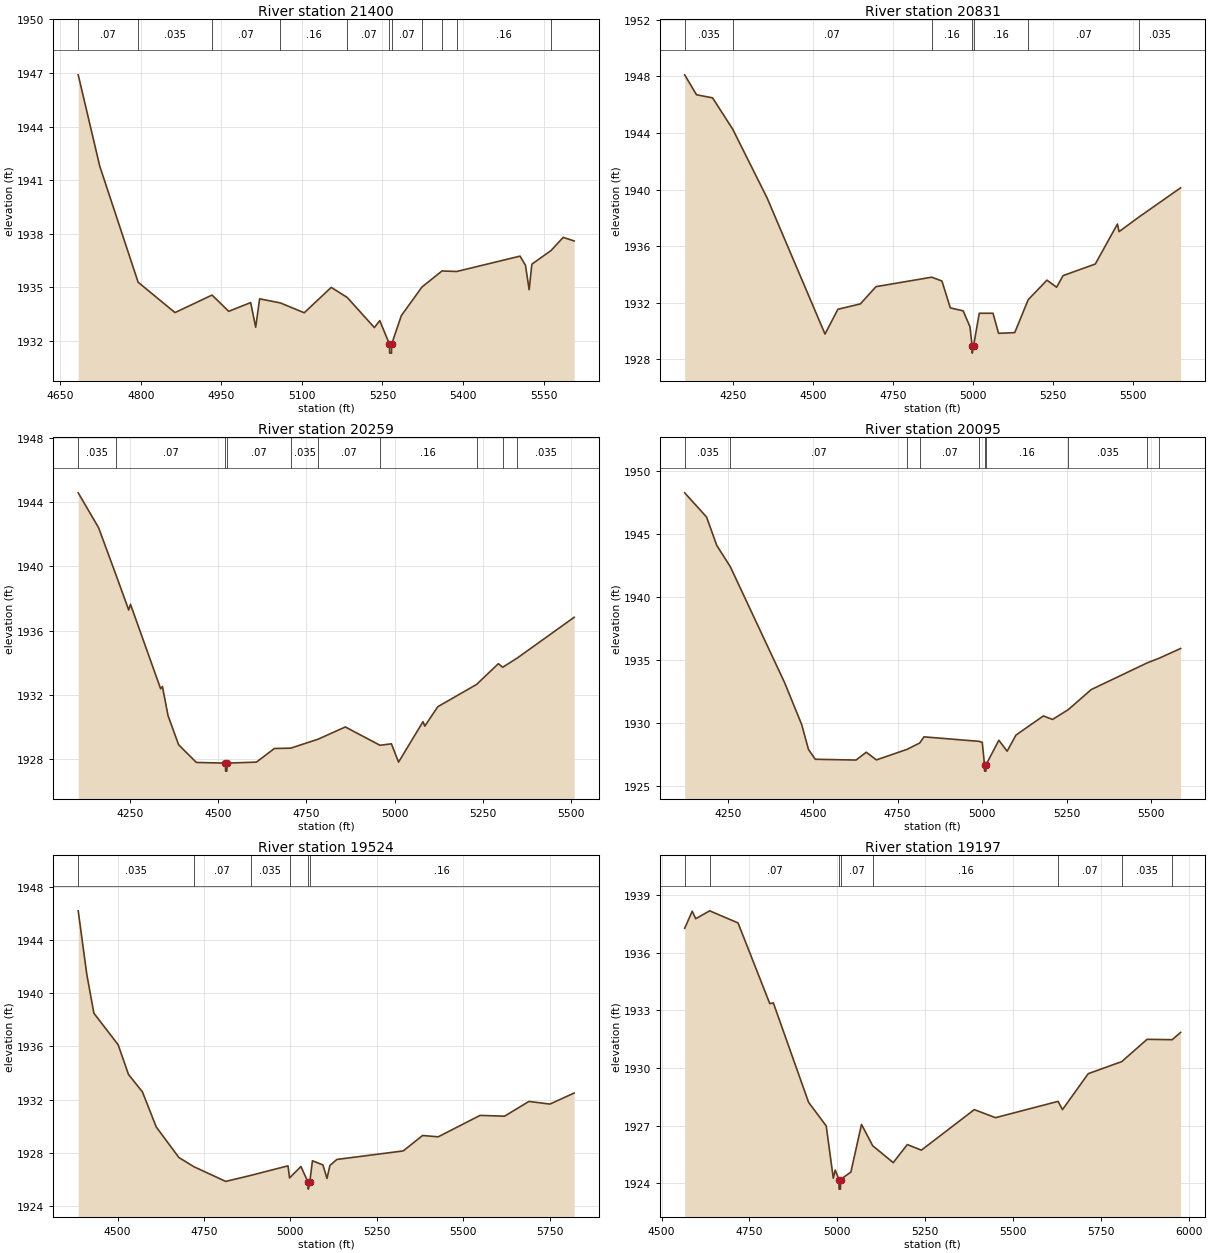
Type RM Length L Ch R = 1 ,21400   ,569,569,569
BEGIN DESCRIPTION:
Elm 01 08 21400.435
END DESCRIPTION:
XS GIS Cut Line= 3
      1560204.99        6779888.      1560521.31      6779905.34
      1561125.29      6779844.83
#Sta/Elev= 30
  4683.2  1946.9  4723.3 1941.79  4794.8 1935.29  4863.5 1933.59  4932.5 1934.57
  4963.6 1933.66  5004.4 1934.15  5013.8 1932.77  5021.1 1934.36  5059.8 1934.13
  5104.2 1933.58  5154.5    1935  5184.2 1934.44  5234.9 1932.75  5244.9 1933.14
    5263 1931.82  5263.3 1931.32  5266.8 1931.32    5267 1931.82  5285.1 1933.42
  5323.5 1935.02  5360.8 1935.92  5388.2 1935.89  5506.2 1936.75  5516.3 1936.24
  5523.2 1934.87  5528.2  1936.3  5563.8 1937.06  5586.6  1937.8    5607  1937.6
#Mann= 11 ,-1 , 0
  4683.2     .07       0  4794.8    .035       0  4932.5     .07       0
  5059.8     .16       0  5184.2     .07       0    5263     .07       0
    5267     .07       0  5323.5     .16       0  5360.8     .07       0
  5388.2     .16       0  5563.8     .07       0
Bank Sta=5263,5267
XS Rating Curve= 0 ,0
Exp/Cntr=0.3,0.1

Type RM Length L Ch R = 1 ,20831   ,572,572,572
BEGIN DESCRIPTION:
Elm 01 08 20830.65
END DESCRIPTION:
XS GIS Cut Line= 3
      1559758.17      6780243.27      1560646.15      6780331.81
      1561299.78      6780248.48
#Sta/Elev= 30
  4098.8 1948.11  4135.8  1946.7  4186.1 1946.48    4249 1944.27  4356.9 1939.39
  4537.8 1929.78    4578 1931.53  4648.3 1931.91  4697.2 1933.13  4871.5  1933.8
  4903.5 1933.53  4929.7 1931.63  4969.9 1931.42  4991.2  1930.3    4998 1928.93
  4998.3 1928.43  5002.3 1928.93  5020.3 1931.25  5063.2 1931.25  5080.7 1929.83
  5131.2 1929.88  5173.4 1932.21    5232 1933.59  5262.2 1933.09  5282.4 1933.91
  5383.2 1934.73  5452.5 1937.56  5457.5 1937.02  5518.9 1938.04  5650.1 1940.12
#Mann= 7 ,-1 , 0
  4098.8    .035       0    4249     .07       0  4871.5     .16       0
    4998     .07       0  5002.3     .16       0  5173.4     .07       0
  5518.9    .035       0
Bank Sta=4998,5002.3
XS Rating Curve= 0 ,0
Exp/Cntr=0.3,0.1

Type RM Length L Ch R = 1 ,20259   ,164,164,164
BEGIN DESCRIPTION:
Elm 01 08 20259.04
END DESCRIPTION:
XS GIS Cut Line= 3
      1559661.79      6780766.71       1560552.4      6780865.67
       1561057.6      6780790.15
#Sta/Elev= 30
  4102.6 1944.58  4160.4 1942.41  4211.1 1939.39  4245.9 1937.28  4250.9 1937.64
  4336.4 1932.38  4341.5 1932.52  4357.4 1930.71  4387.5 1928.89  4437.9 1927.79
  4520.4 1927.75  4520.7 1927.25  4524.4 1927.25  4524.7 1927.75  4608.1 1927.81
  4659.2 1928.66  4705.5 1928.68  4783.3 1929.24  4860.4    1930  4958.7 1928.86
  4991.2 1928.95  5011.4 1927.81  5080.8 1930.33  5085.8 1930.05  5122.6 1931.26
  5232.8 1932.65  5294.5 1933.94  5306.8 1933.72    5348 1934.29  5509.5 1936.83
#Mann= 10 ,-1 , 0
  4102.6    .035       0  4211.1     .07       0  4520.4     .07       0
  4524.7     .07       0  4705.5    .035       0  4783.3     .07       0
  4958.7     .16       0  5232.8    .035       0  5306.8     .07       0
    5348    .035       0
Bank Sta=4520.4,4524.7
XS Rating Curve= 0 ,0
Exp/Cntr=0.3,0.1

Type RM Length L Ch R = 1 ,20095   ,571,571,571
BEGIN DESCRIPTION:
Elm 01 08 20095.28
END DESCRIPTION:
XS GIS Cut Line= 3
      1559630.53      6780938.58      1560502.92       6781014.1
      1561086.28      6780928.16
#Sta/Elev= 30
    4121 1948.26  4185.7 1946.34  4215.8 1944.09  4255.8  1942.4  4416.6 1933.18
  4466.8 1929.87  4486.8  1927.9  4506.9 1927.12  4627.4 1927.06  4657.5 1927.68
  4687.6 1927.07  4778.2 1927.91  4815.4 1928.41  4828.1  1928.9  4991.5 1928.54
  5000.2 1928.46  5006.9 1926.68  5007.2 1926.18  5010.9 1926.18  5011.2 1926.68
  5049.3 1928.63  5073.7 1927.76  5099.8 1929.04  5180.7 1930.56    5208 1930.28
  5254.4 1931.06  5322.2 1932.65  5486.9 1934.76  5523.9 1935.15  5586.3 1935.91
#Mann= 10 ,-1 , 0
    4121    .035       0  4255.8     .07       0  4778.2    .035       0
  4815.4     .07       0  4991.5     .16       0  5006.9     .07       0
  5011.2     .16       0  5254.4    .035       0  5486.9     .07       0
  5523.9    .035       0
Bank Sta=5006.9,5011.2
XS Rating Curve= 0 ,0
Exp/Cntr=0.3,0.1

Type RM Length L Ch R = 1 ,19524   ,327,327,327
BEGIN DESCRIPTION:
Elm 01 08 19523.91
END DESCRIPTION:
XS GIS Cut Line= 3
      1559739.86      6781430.77      1560351.88      6781477.64
      1561164.36      6781360.46
#Sta/Elev= 30
  4386.3 1946.19    4411 1941.44  4431.6  1938.5  4501.8 1936.13  4531.9 1933.89
    4572 1932.59  4612.1 1929.95  4677.4 1927.66  4720.5 1926.97    4813 1925.86
  4885.2 1926.31  4993.2 1927.03  4997.7 1926.12  5030.6 1926.98  5051.6 1925.78
  5051.9 1925.28    5056 1925.78  5063.9 1927.41  5094.2  1927.1    5106 1926.08
  5114.4 1927.06  5134.6 1927.51  5326.6 1928.15  5382.5 1929.31  5427.6 1929.21
  5548.9 1930.82  5619.6 1930.76  5690.3 1931.87  5750.9 1931.67    5821  1932.5
#Mann= 6 ,-1 , 0
  4386.3    .035       0  4720.5     .07       0  4885.2    .035       0
  4997.7     .16       0  5051.6     .07       0    5056     .16       0
Bank Sta=5051.6,5056
XS Rating Curve= 0 ,0
Exp/Cntr=0.3,0.1

Type RM Length L Ch R = 1 ,19197   ,445,445,445
BEGIN DESCRIPTION:
Elm 01 08 19196.81
END DESCRIPTION:
XS GIS Cut Line= 3
      1559773.73      6781714.62      1560208.65      6781753.69
      1561180.02      6781670.35
#Sta/Elev= 30
  4565.8 1937.27  4587.2 1938.16  4597.2 1937.77    4637 1938.18  4717.7 1937.55
    4808 1933.35  4818.1 1933.39  4918.5 1928.21  4968.7 1926.98  4988.8 1924.26
  4994.3 1924.68  5004.9 1924.19  5005.3 1923.69  5009.1 1923.69  5009.4 1924.19
  5038.9 1924.58  5069.1 1927.06  5100.9 1925.95  5159.4 1925.07  5199.5 1926.01
  5239.6 1925.72  5390.2 1927.83  5450.5 1927.41  5628.6 1928.26  5641.2 1927.83
  5714.4  1929.7  5809.9 1930.33    5882 1931.49  5953.3 1931.47  5977.4 1931.85
#Mann= 8 ,-1 , 0
  4565.8    .035       0    4637     .07       0  5004.9     .07       0
  5009.4     .07       0  5100.9     .16       0  5628.6     .07       0
  5809.9    .035       0  5953.3     .07       0
Bank Sta=5004.9,5009.4
XS Rating Curve= 0 ,0
Exp/Cntr=0.3,0.1

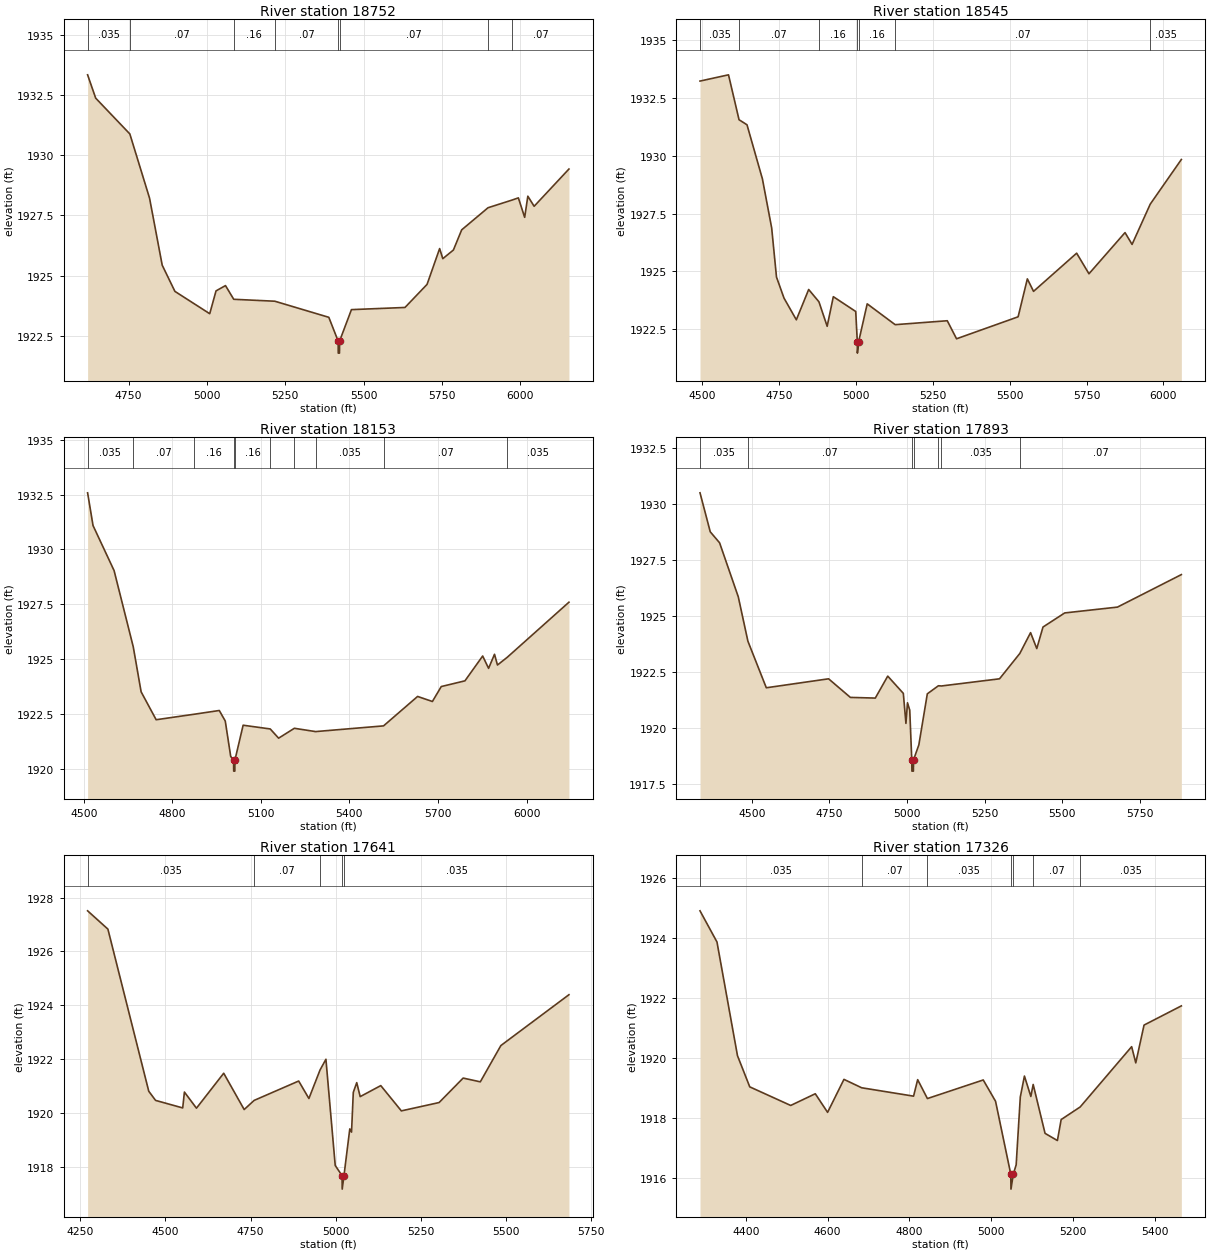
Type RM Length L Ch R = 1 ,18752   ,207,207,207
BEGIN DESCRIPTION:
Elm 01 08 18751.57
END DESCRIPTION:
XS GIS Cut Line= 3
      1559729.52      6782105.25       1560109.7      6782162.54
      1561255.55      6782045.35
#Sta/Elev= 30
  4619.2 1933.35    4645 1932.38    4754 1930.89  4816.9 1928.22  4857.3 1925.43
  4897.8 1924.34    5009 1923.41  5029.1 1924.36  5059.3 1924.58  5085.6 1924.01
  5216.7 1923.93  5389.1 1923.26  5418.9 1922.27  5419.2 1921.77  5423.1 1921.77
  5423.4 1922.27  5461.3 1923.58  5632.2 1923.67  5702.6 1924.63  5742.8 1926.12
  5752.9  1925.7  5786.7 1926.06  5813.2  1926.9  5897.3 1927.82  5974.2 1928.14
  5994.1 1928.23  6014.2 1927.42  6024.3  1928.3  6044.4 1927.88  6155.5 1929.43
#Mann= 8 ,-1 , 0
  4619.2    .035       0    4754     .07       0  5085.6     .16       0
  5216.7     .07       0  5418.9     .07       0  5423.4     .07       0
  5897.3    .035       0  5974.2     .07       0
Bank Sta=5418.9,5423.4
XS Rating Curve= 0 ,0
Exp/Cntr=0.3,0.1

Type RM Length L Ch R = 1 ,18545   ,392,392,392
BEGIN DESCRIPTION:
Elm 01 08 18545.43
END DESCRIPTION:
XS GIS Cut Line= 3
       1559742.5      6782258.89      1560247.72      6782287.54
      1561304.97      6782245.88
#Sta/Elev= 30
  4494.1 1933.23  4586.7  1933.5  4620.9 1931.56  4646.8 1931.34  4696.9    1929
    4727 1926.88  4742.6 1924.76    4767 1923.85  4807.1 1922.91  4847.2 1924.22
  4880.5 1923.69  4907.3 1922.63  4927.3 1923.91  5000.1 1923.27  5005.2 1921.97
  5005.5 1921.47  5009.7 1921.97  5037.4  1923.6  5128.3  1922.7  5297.6 1922.87
  5327.7 1922.09  5527.8 1923.04  5557.8 1924.68  5577.9 1924.14    5718 1925.79
    5758  1924.9  5875.2 1926.68  5898.1 1926.17  5957.1 1927.91  6058.2 1929.84
#Mann= 7 ,-1 , 0
  4494.1    .035       0  4620.9     .07       0  4880.5     .16       0
  5005.2     .07       0  5009.7     .16       0  5128.3     .07       0
  5957.1    .035       0
Bank Sta=5005.2,5009.7
XS Rating Curve= 0 ,0
Exp/Cntr=0.3,0.1

Type RM Length L Ch R = 1 ,18153   ,260,260,260
BEGIN DESCRIPTION:
Elm 01 08 18153.07
END DESCRIPTION:
XS GIS Cut Line= 3
      1559726.89       6782451.6      1560206.05      6782542.75
      1561346.69      6782475.04
#Sta/Elev= 30
  4513.2 1932.58  4531.6 1931.09  4602.9 1929.04  4667.8 1925.57  4694.5 1923.52
  4745.4 1922.25  4874.2  1922.5  4959.2 1922.67  4979.5 1922.19  4997.9 1920.58
  5007.7 1920.41    5008 1919.91  5011.9 1919.91  5012.2 1920.41    5040    1922
  5131.8 1921.83  5160.2 1921.41  5213.5 1921.86  5285.4 1921.71  5515.6 1921.97
    5631 1923.31  5681.1 1923.08  5711.1 1923.76  5791.3 1924.02  5851.4 1925.15
  5871.4 1924.59  5891.5 1925.23  5901.5 1924.74  5934.4 1925.09  6143.6  1927.6
#Mann= 10 ,-1 , 0
  4513.2    .035       0  4667.8     .07       0  4874.2     .16       0
  5007.7     .07       0  5012.2     .16       0  5131.8    .035       0
  5213.5     .16       0  5285.4    .035       0  5515.6     .07       0
  5934.4    .035       0
Bank Sta=5007.7,5012.2
XS Rating Curve= 0 ,0
Exp/Cntr=0.3,0.1

Type RM Length L Ch R = 1 ,17893   ,252,252,252
BEGIN DESCRIPTION:
Elm 01 08 17892.75
END DESCRIPTION:
XS GIS Cut Line= 3
      1559732.12      6782628.69      1560401.36      6782683.37
      1561280.78      6782678.17
#Sta/Elev= 30
  4332.9 1930.49  4365.9 1928.75    4396 1928.26  4456.2 1925.85  4487.2 1923.87
  4546.5 1921.79  4747.2 1922.19  4817.4 1921.36  4897.7 1921.33  4937.8 1922.31
    4988 1921.54  4996.4  1920.2  5001.4 1921.12  5008.7 1920.79  5015.2 1918.57
  5015.7 1918.07  5020.4 1918.07  5020.8 1918.57    5038 1919.24  5065.3 1921.52
  5101.1 1921.88  5110.7 1921.87    5298 1922.19  5363.3 1923.32    5398 1924.25
    5418 1923.54    5438  1924.5    5508 1925.13    5678 1925.39  5883.8 1926.84
#Mann= 7 ,-1 , 0
  4332.9    .035       0  4487.2     .07       0  5015.2     .07       0
  5020.8     .07       0  5101.1     .16       0  5110.7    .035       0
  5363.3     .07       0
Bank Sta=5015.2,5020.8
XS Rating Curve= 0 ,0
Exp/Cntr=0.3,0.1

Type RM Length L Ch R = 1 ,17641   ,315,315,315
BEGIN DESCRIPTION:
Elm 01 08 17641.29
END DESCRIPTION:
XS GIS Cut Line= 3
      1559815.46      6782902.12      1560544.59      6782878.69
      1561223.28      6782792.88
#Sta/Elev= 30
  4271.6 1927.51  4331.2 1926.83  4451.2  1920.8  4471.2 1920.46  4550.9 1920.18
  4555.9 1920.77  4591.3 1920.17  4671.3 1921.47  4731.4 1920.12  4760.7 1920.46
  4891.5 1921.18  4921.5 1920.53  4954.2 1921.59  4971.5 1921.99  4998.8 1918.04
  5018.9 1917.66  5019.3 1917.16  5024.5 1917.66  5041.6  1919.4  5046.7 1919.28
  5051.9 1920.76    5062 1921.12  5072.1  1920.6  5132.6 1921.01    5193 1920.07
  5303.9 1920.38  5374.5 1921.29  5424.9 1921.15  5485.3  1922.5  5685.2 1924.39
#Mann= 5 ,-1 , 0
  4271.6    .035       0  4760.7     .07       0  4954.2    .035       0
  5018.9    .035       0  5024.5    .035       0
Bank Sta=5018.9,5024.5
XS Rating Curve= 0 ,0
Exp/Cntr=0.3,0.1

Type RM Length L Ch R = 1 ,17326   ,448,448,448
BEGIN DESCRIPTION:
Elm 01 08 17325.94
END DESCRIPTION:
XS GIS Cut Line= 3
      1559893.55       6783139.1      1560604.49      6783175.56
      1561065.44      6783115.66
#Sta/Elev= 30
  4287.9  1924.9  4329.4 1923.86  4379.5 1920.07  4409.5 1919.03  4509.6 1918.41
  4569.7  1918.8  4599.8 1918.18  4639.8 1919.28    4683    1919    4810 1918.72
    4820 1919.27  4843.8 1918.64  4980.3 1919.26  5010.4 1918.55  5047.6 1916.12
  5048.1 1915.62  5053.8 1916.12  5060.8 1916.43  5070.9 1918.69    5081 1919.39
  5096.7 1918.71  5102.4 1919.11  5131.4 1917.48  5161.6 1917.24  5170.8 1917.94
  5217.3 1918.36  5343.1 1920.37  5353.2 1919.83  5373.4 1921.09  5464.6 1921.73
#Mann= 7 ,-1 , 0
  4287.9    .035       0    4683     .07       0  4843.8    .035       0
  5047.6    .035       0  5053.8    .035       0  5102.4     .07       0
  5217.3    .035       0
Bank Sta=5047.6,5053.8
XS Rating Curve= 0 ,0
Exp/Cntr=0.3,0.1

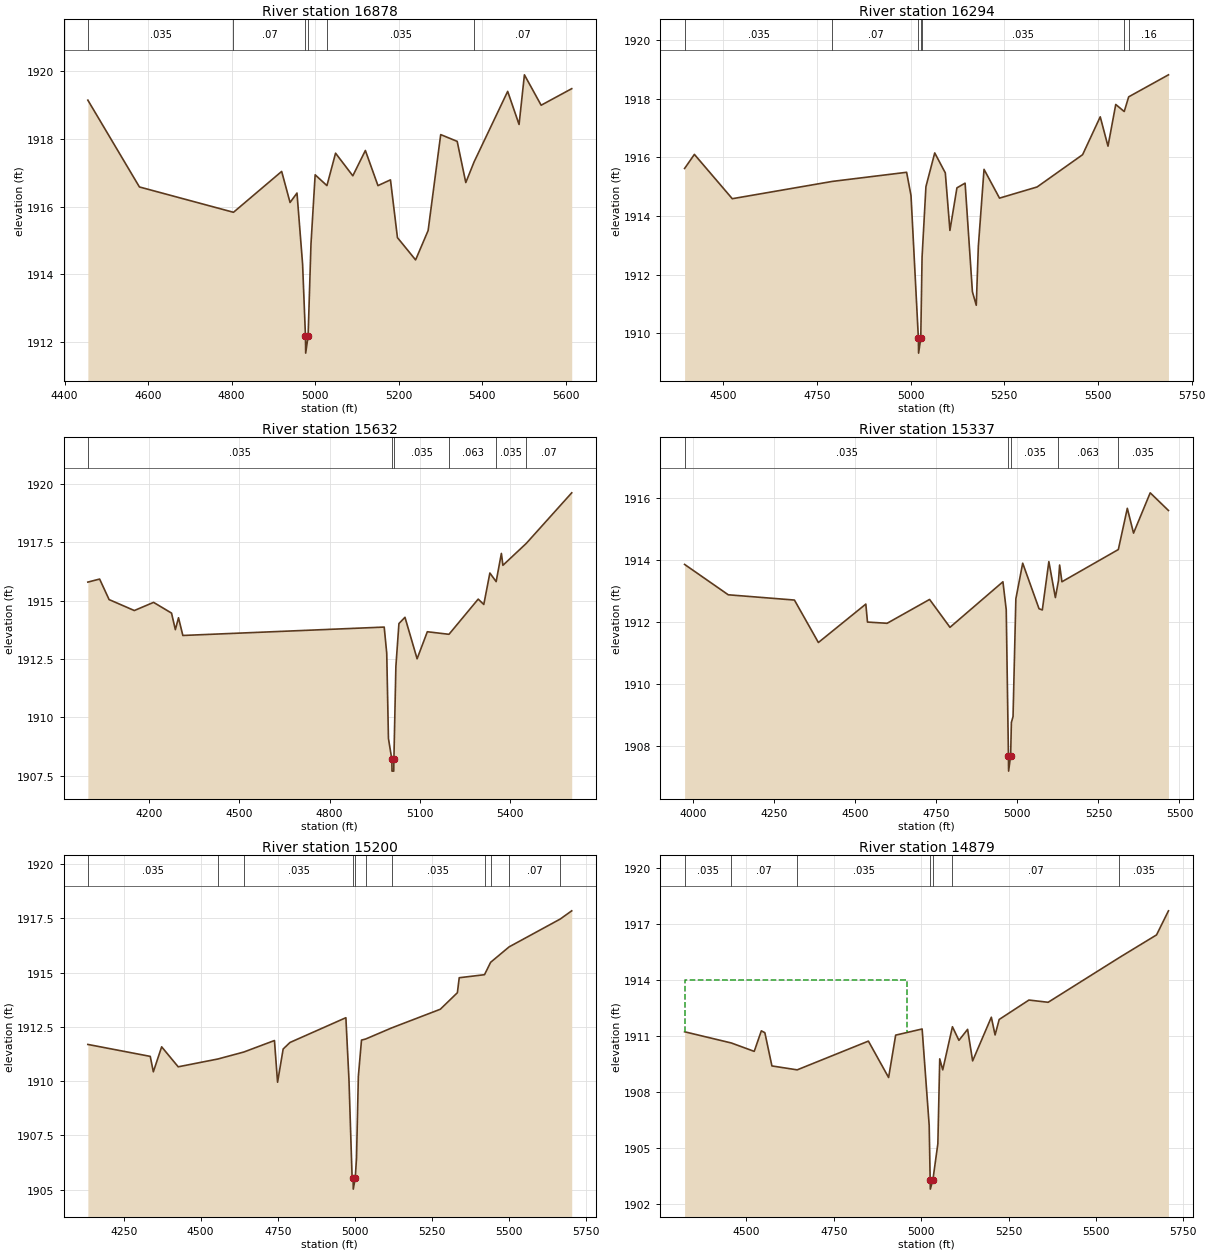
Type RM Length L Ch R = 1 ,16878   ,584,584,584
BEGIN DESCRIPTION:
Elm 01 08 16877.92
END DESCRIPTION:
XS GIS Cut Line= 3
      1559911.79      6783529.73      1560461.26      6783566.19
      1561068.06      6783524.52
#Sta/Elev= 30
  4455.7 1919.15  4579.2 1916.58  4804.5 1915.83  4919.9 1917.04    4940 1916.12
  4956.6  1916.4    4970  1914.3  4976.9 1912.16  4977.4 1911.66  4983.2 1912.16
  4990.1 1914.89  5000.1 1916.94  5028.3 1916.62    5049 1917.58  5090.3 1916.91
  5120.4 1917.66  5150.5 1916.62  5180.5 1916.79  5197.2 1915.08  5240.7 1914.42
  5270.7 1915.29  5300.8 1918.13  5340.3 1917.93  5360.9 1916.71  5380.7 1917.32
  5461.2 1919.41  5488.5 1918.43  5501.3  1919.9  5541.4    1919  5614.6 1919.49
#Mann= 6 ,-1 , 0
  4455.7    .035       0  4804.5     .07       0  4976.9     .07       0
  4983.2     .07       0  5028.3    .035       0  5380.7     .07       0
Bank Sta=4976.9,4983.2
XS Rating Curve= 0 ,0
Exp/Cntr=0.3,0.1

Type RM Length L Ch R = 1 ,16294   ,662,662,662
BEGIN DESCRIPTION:
Elm 01 08 16293.75
END DESCRIPTION:
XS GIS Cut Line= 3
      1559909.19      6783930.77      1560502.92      6784019.31
      1561171.09      6783845.12
#Sta/Elev= 30
  4397.3 1915.62  4423.4  1916.1  4524.5 1914.59  4791.8 1915.18  4989.6 1915.49
  5001.3  1914.7    5021 1909.83  5021.5 1909.33  5027.3 1909.83  5029.8 1911.81
  5030.8  1912.6  5041.1    1915  5064.6 1916.15  5092.8 1915.47  5105.1 1913.51
  5123.8 1914.96  5145.6 1915.12  5165.1 1911.42  5175.4 1910.96  5180.9 1912.96
  5196.1 1915.59  5237.4 1914.61  5337.7 1914.99  5459.1 1916.09  5506.1 1917.38
  5526.8 1916.38  5547.5  1917.8  5570.1 1917.56    5582 1918.06  5688.1 1918.81
#Mann= 7 ,-1 , 0
  4397.3    .035       0  4791.8     .07       0    5021     .07       0
  5027.3     .07       0  5029.8    .035       0  5570.1     .07       0
    5582     .16       0
Bank Sta=5021,5027.3
XS Rating Curve= 0 ,0
Exp/Cntr=0.3,0.1

Type RM Length L Ch R = 1 ,15632   ,295,295,295
BEGIN DESCRIPTION:
Elm 01 08 15631.64
END DESCRIPTION:
XS GIS Cut Line= 3
      1559747.69      6784068.78      1560700.84      6784368.27
      1561304.97      6784295.36
#Sta/Elev= 30
  3996.9  1915.8    4036 1915.93  4067.5 1915.05  4151.3 1914.58  4215.3 1914.93
  4274.9 1914.47  4287.6 1913.76  4298.1 1914.27  4312.5 1913.51  4981.5 1913.87
  4989.9 1912.75  4995.6 1909.09  5006.9 1908.19  5007.4 1907.69  5013.2 1907.69
  5013.7 1908.19  5020.3 1912.18  5030.4 1914.02  5050.5 1914.29  5090.8 1912.51
  5124.8 1913.67  5196.7 1913.56  5293.8 1915.07  5312.4 1914.84  5332.6 1916.19
  5353.4 1915.82  5370.8 1917.03  5375.9 1916.52  5453.5 1917.46  5604.5 1919.63
#Mann= 6 ,-1 , 0
  3996.9    .035       0  5006.9    .035       0  5013.7    .035       0
  5196.7    .063       0  5353.4    .035       0  5453.5     .07       0
Bank Sta=5006.9,5013.7
XS Rating Curve= 0 ,0
Exp/Cntr=0.3,0.1

Type RM Length L Ch R = 1 ,15337   ,137,137,137
BEGIN DESCRIPTION:
Elm 01 08 15336.85
END DESCRIPTION:
XS GIS Cut Line= 3
      1559693.06      6784430.78      1560698.24       6784636.5
      1561160.88      6784696.28
#Sta/Elev= 30
  3973.6 1913.87  4108.3 1912.89  4312.4 1912.72  4386.3 1911.35  4532.6 1912.59
  4537.7 1912.01  4598.2 1911.97  4729.3 1912.74  4792.2 1911.84  4955.5 1913.31
  4965.7 1912.41  4972.5  1907.7    4973  1907.2  4979.3  1907.7  4981.6 1908.77
  4986.7 1908.96  4995.4 1912.76  5016.5 1913.91  5066.9 1912.44    5077  1912.4
  5097.2 1913.96  5117.3  1912.8  5126.9 1913.35  5130.4 1913.85  5137.5 1913.31
  5311.5 1914.35  5339.2 1915.68  5358.4 1914.88  5409.8 1916.18  5466.1 1915.61
#Mann= 5 ,-1 , 0
  3973.6    .035       0  4972.5    .035       0  4979.3    .035       0
  5126.9    .063       0  5311.5    .035       0
Bank Sta=4972.5,4979.3
XS Rating Curve= 0 ,0
Exp/Cntr=0.3,0.1

Type RM Length L Ch R = 1 ,15200   ,321,321,321
BEGIN DESCRIPTION:
Elm 01 08 15200.32
END DESCRIPTION:
XS GIS Cut Line= 3
      1559844.05      6784662.54      1560703.45      6784771.92
      1561391.73      6784922.56
#Sta/Elev= 30
  4133.7 1911.69  4336.3 1911.14  4346.3 1910.43  4373.3 1911.58    4427 1910.66
  4555.9 1911.02  4639.9 1911.34  4739.5 1911.87  4749.6 1909.95  4767.8 1911.48
  4789.9 1911.78  4971.4 1912.92  4981.4 1910.08  4991.5 1905.61  4994.9 1905.53
  4995.4 1905.03  5001.7 1905.53  5005.9 1906.45  5011.9 1910.22  5022.1 1911.89
  5035.7 1911.94  5119.9 1912.45    5278 1913.31  5333.4 1914.07  5339.4 1914.76
  5421.5  1914.9  5441.3 1915.47  5501.3 1916.18  5667.1 1917.46  5704.6 1917.84
#Mann= 11 ,-1 , 0
  4133.7    .035       0  4555.9     .07       0  4639.9    .035       0
  4994.9    .035       0  5001.7    .035       0  5035.7    .063       0
  5119.9    .035       0  5421.5     .07       0  5441.3    .035       0
  5501.3     .07       0  5667.1    .035       0
Bank Sta=4994.9,5001.7
XS Rating Curve= 0 ,0
Exp/Cntr=0.3,0.1

Type RM Length L Ch R = 1 ,14879   ,444,444,444
BEGIN DESCRIPTION:
Elm 01 08 14878.69
END DESCRIPTION:
XS GIS Cut Line= 3
      1559817.99      6784904.72       1560489.9      6785006.29
      1561148.72      6785256.28
#Sta/Elev= 30
  4323.2 1911.21  4456.9 1910.61  4522.4 1910.16  4542.7 1911.26  4552.8 1911.16
    4573 1909.38  4645.3 1909.17    4849 1910.71  4906.8 1908.76    4927 1911.03
  5002.7 1911.36  5022.9  1906.2  5025.7 1903.28  5026.2 1902.78  5033.5 1903.28
  5047.7 1905.21  5053.1 1909.76  5061.7 1909.17  5089.4 1911.48    5108 1910.75
  5132.8 1911.34  5147.2 1909.65  5200.7 1911.99  5211.4 1911.04  5223.2 1911.87
  5308.3 1912.91  5363.2 1912.79  5567.2 1915.19  5673.3  1916.4  5707.4 1917.69
#Mann= 7 ,-1 , 0
  4323.2    .035       0  4456.9     .07       0  4645.3    .035       0
  5025.7    .035       0  5033.5    .035       0  5089.4     .07       0
  5567.2    .035       0
#XS Ineff= 2 , 0
       0    4960    1914               0
Permanent Ineff=
       F       F
Bank Sta=5025.7,5033.5
XS Rating Curve= 0 ,0
Exp/Cntr=0.3,0.1

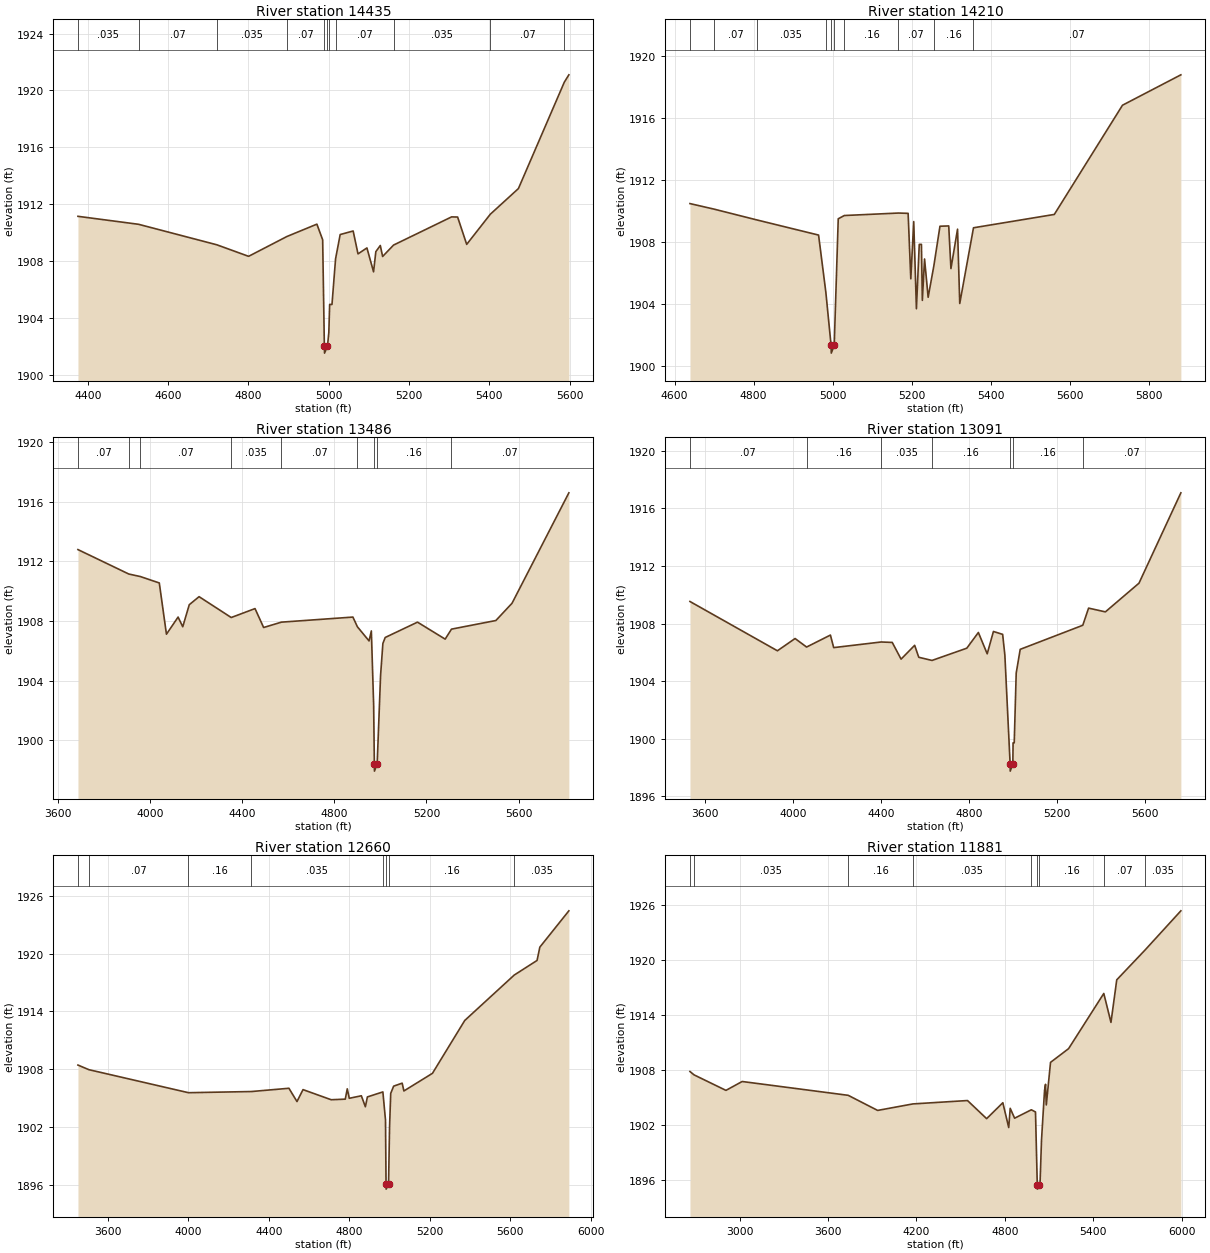
Type RM Length L Ch R = 1 ,14435   ,225,225,225
BEGIN DESCRIPTION:
Elm 01 08 14435.18
END DESCRIPTION:
XS GIS Cut Line= 3
      1559828.47       6784938.6      1560323.24       6785326.6
      1560858.21       6785583.7
#Sta/Elev= 30
  4375.7 1911.16  4526.6  1910.6  4721.5 1909.16  4800.6 1908.35  4895.8 1909.74
  4970.6 1910.61    4985 1909.51  4989.2 1902.05  4989.7 1901.55    4997 1902.05
  5000.3 1902.99  5002.4 1904.97  5008.2 1904.97  5017.1 1908.17  5028.6 1909.88
  5060.9 1910.13    5073 1908.52  5095.2 1908.94  5111.7 1907.26  5117.4 1908.68
  5128.5 1909.11  5134.3 1908.34  5161.5 1909.14    5306 1911.12    5321 1911.11
  5343.6 1909.19  5402.5 1911.31  5472.4 1913.11  5586.6 1920.58    5598  1921.1
#Mann= 11 ,-1 , 0
  4375.7    .035       0  4526.6     .07       0  4721.5    .035       0
  4895.8     .07       0  4989.2     .07       0    4997     .07       0
  5000.3     .16       0  5017.1     .07       0  5161.5    .035       0
  5402.5     .07       0  5586.6    .035       0
Bank Sta=4989.2,4997
XS Rating Curve= 0 ,0
Exp/Cntr=0.3,0.1

Type RM Length L Ch R = 1 ,14210   ,724,724,724
BEGIN DESCRIPTION:
Elm 01 08 14209.55
END DESCRIPTION:
XS GIS Cut Line= 3
      1559901.38      6785131.31       1560299.8      6785560.98
      1560885.72      6785857.84
#Sta/Elev= 30
  4638.9 1910.47  4700.3 1910.11  4807.6 1909.42  4964.5 1908.44  4982.9 1904.76
  4996.2 1901.33  4996.7 1900.83  5004.1 1901.33  5014.3 1909.49  5029.7  1909.7
  5166.7 1909.86  5191.2 1909.84    5198 1905.62  5205.4 1909.31  5212.2 1903.69
  5219.4 1907.84  5224.9 1907.84  5227.2 1904.23  5232.8  1906.9  5241.9 1904.43
  5256.3 1906.45  5271.8 1909.01    5294 1909.03  5299.6 1906.28  5316.3 1908.82
  5321.9 1904.03  5356.7 1908.91  5561.3 1909.77  5733.9 1916.81  5881.7 1918.77
#Mann= 10 ,-1 , 0
  4638.9    .035       0  4700.3     .07       0  4807.6    .035       0
  4982.9     .07       0  4996.2     .07       0  5004.1     .07       0
  5029.7     .16       0  5166.7     .07       0  5256.3     .16       0
  5356.7     .07       0
Bank Sta=4996.2,5004.1
XS Rating Curve= 0 ,0
Exp/Cntr=0.3,0.1

Type RM Length L Ch R = 1 ,13486   ,395,395,395
BEGIN DESCRIPTION:
Elm 01 08 13485.69
END DESCRIPTION:
XS GIS Cut Line= 3
      1558755.49      6785847.43      1559914.38      6786029.73
      1560871.33      6785977.72
#Sta/Elev= 30
  3686.7 1912.79  3907.4 1911.15  3957.7 1910.98  4039.9 1910.55  4070.9 1907.11
  4121.5 1908.26  4141.7 1907.61    4170 1909.09  4212.6 1909.63  4352.2 1908.23
  4455.5 1908.83  4492.9 1907.56  4570.2 1907.92  4880.5 1908.26    4900 1907.61
  4950.6 1906.66  4960.6 1907.33  4970.6 1902.35  4973.6 1898.42  4974.1 1897.92
  4985.9 1898.42  5000.7 1904.36  5010.7 1906.49  5020.7 1906.89  5160.9 1907.92
  5281.1 1906.78  5308.5 1907.45  5501.4 1908.03  5571.5 1909.19  5818.2  1916.6
#Mann= 9 ,-1 , 0
  3686.7     .07       0  3907.4     .16       0  3957.7     .07       0
  4352.2    .035       0  4570.2     .07       0    4900     .16       0
  4973.6     .07       0  4985.9     .16       0  5308.5     .07       0
Bank Sta=4973.6,4985.9
XS Rating Curve= 0 ,0
Exp/Cntr=0.3,0.1

Type RM Length L Ch R = 1 ,13091   ,431,431,431
BEGIN DESCRIPTION:
Elm 01 08 13091.42
END DESCRIPTION:
XS GIS Cut Line= 3
      1558718.97      6786486.73      1560184.38      6786365.74
      1560883.81      6786067.89
#Sta/Elev= 30
  3531.1 1909.53  3928.5 1906.11  4008.7 1906.96  4061.1 1906.37  4169.3  1907.2
  4184.2 1906.33  4399.8 1906.72  4450.2 1906.69  4490.4 1905.53  4552.1 1906.49
  4570.7 1905.66  4630.9 1905.44    4789 1906.29  4841.6 1907.38  4881.7  1905.9
    4910 1907.45  4951.9 1907.25    4962 1905.81  4985.9 1898.26  4986.4 1897.76
  4998.2 1898.26  4999.3 1899.72  5004.5 1899.72  5013.5 1904.56  5031.7 1906.21
    5316 1907.88  5342.4 1909.07  5418.7 1908.81  5571.4  1910.8  5761.7 1917.07
#Mann= 7 ,-1 , 0
  3531.1     .07       0  4061.1     .16       0  4399.8    .035       0
  4630.9     .16       0  4985.9     .07       0  4998.2     .16       0
    5316     .07       0
Bank Sta=4985.9,4998.2
XS Rating Curve= 0 ,0
Exp/Cntr=0.3,0.1

Type RM Length L Ch R = 1 ,12660   ,779,779,779
BEGIN DESCRIPTION:
Elm 01 08 12659.86
END DESCRIPTION:
XS GIS Cut Line= 3
      1558656.31      6786778.02      1560197.83      6786755.61
      1561080.28      6786585.39
#Sta/Elev= 30
  3450.9 1908.42  3505.1 1907.94  4000.3 1905.55  4312.7 1905.67  4499.7 1906.01
  4539.7 1904.63  4569.7 1905.87  4709.7 1904.82  4779.7 1904.88  4789.7 1905.95
  4799.7 1904.97  4859.7 1905.23  4879.7 1904.09  4889.7 1905.11  4966.7 1905.63
  4979.8  1902.7  4982.5 1896.04    4983 1895.54  4994.9 1896.04  4999.9 1901.97
  5005.7 1905.48  5020.3 1906.23  5062.6 1906.54  5071.2 1905.73  5213.1 1907.56
  5373.8 1913.05  5619.6 1917.76  5733.2 1919.28    5747 1920.66  5891.3 1924.43
#Mann= 8 ,-1 , 0
  3450.9    .035       0  3505.1     .07       0  4000.3     .16       0
  4312.7    .035       0  4966.7     .16       0  4982.5     .07       0
  4994.9     .16       0  5619.6    .035       0
Bank Sta=4982.5,4994.9
XS Rating Curve= 0 ,0
Exp/Cntr=0.3,0.1

Type RM Length L Ch R = 1 ,11881   ,617,617,617
BEGIN DESCRIPTION:
Elm 01 08 11880.77
END DESCRIPTION:
XS GIS Cut Line= 3
      1557970.66      6787441.25      1560233.68      6787414.36
      1561281.18      6787195.02
#Sta/Elev= 30
  2661.9 1907.84  2690.3 1907.47  2906.3 1905.78  3016.3 1906.75  3736.3 1905.24
  3936.3 1903.59  4175.5  1904.3  4546.4 1904.67  4676.4 1902.69  4786.4 1904.43
  4826.4 1901.72  4836.4 1903.82  4866.4 1902.74    4980 1903.66  5008.2 1903.42
  5020.2 1895.49  5020.7 1894.99  5032.7 1895.49  5038.8  1895.5    5049 1900.36
  5069.5 1905.76  5076.3 1906.44  5081.5 1904.19  5110.3 1908.84  5232.9 1910.34
  5471.9 1916.37  5520.7 1913.21  5559.9 1917.86  5752.3 1921.12  5995.3  1925.4
#Mann= 9 ,-1 , 0
  2661.9    .094       0  2690.3    .035       0  3736.3     .16       0
  4175.5    .035       0    4980     .16       0  5020.2     .07       0
  5032.7     .16       0  5471.9     .07       0  5752.3    .035       0
Bank Sta=5020.2,5032.7
XS Rating Curve= 0 ,0
Exp/Cntr=0.3,0.1

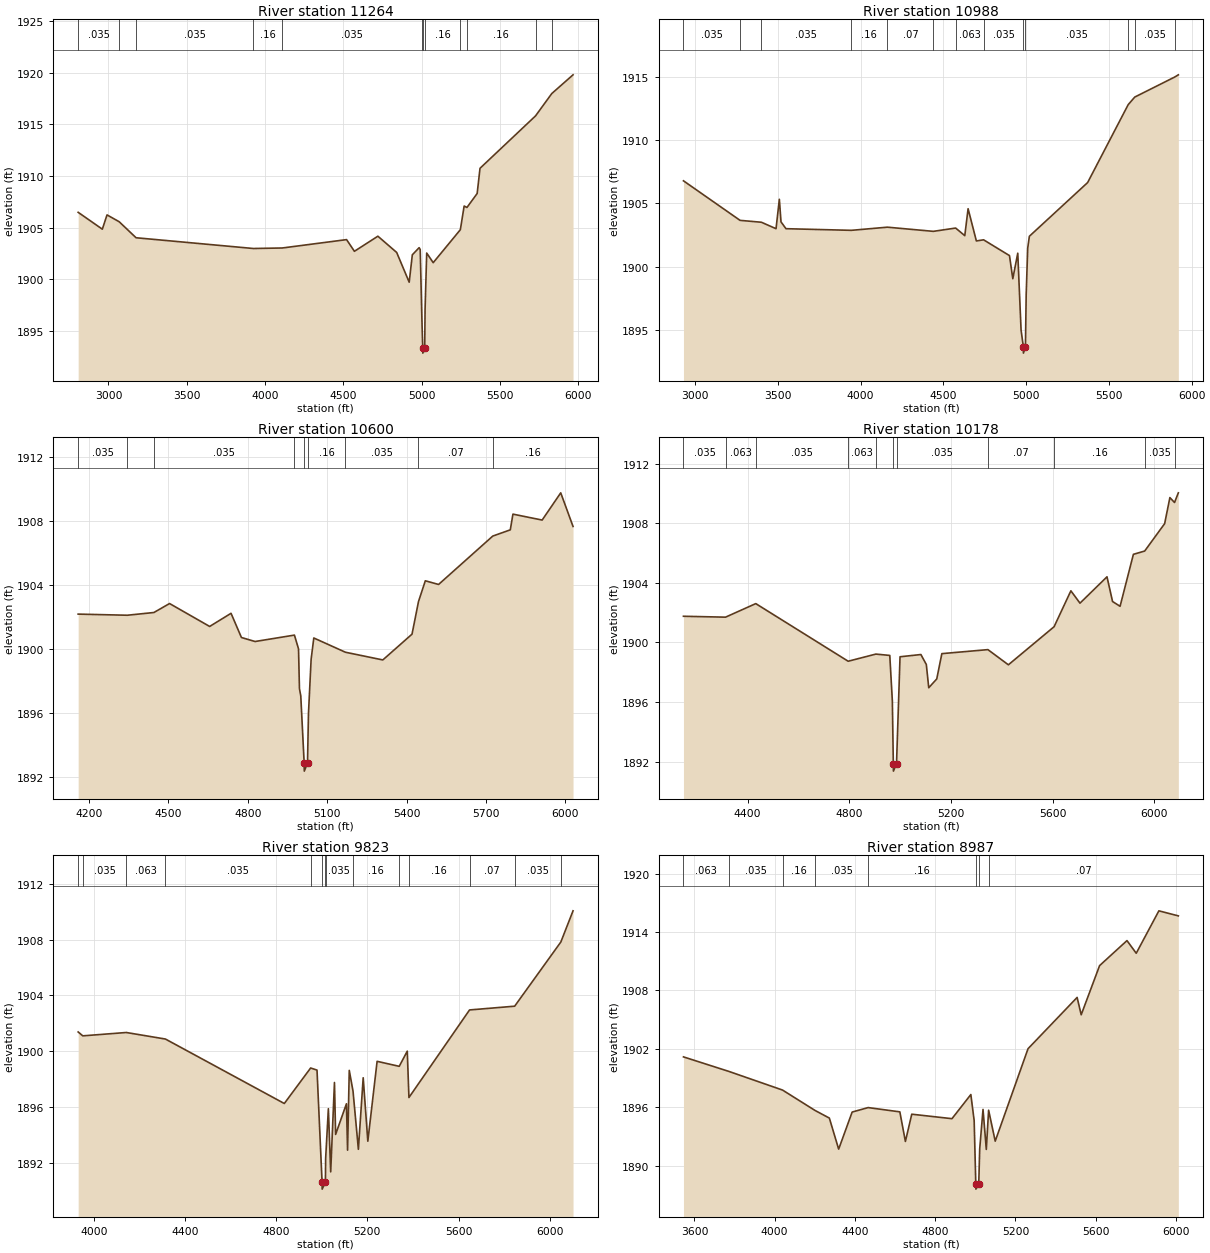
Type RM Length L Ch R = 1 ,11264   ,276,276,276
BEGIN DESCRIPTION:
Elm 01 08 11264.46
END DESCRIPTION:
XS GIS Cut Line= 3
      1557970.57      6787866.98      1560148.53      6787840.09
      1561094.12       6787571.2
#Sta/Elev= 30
  2806.4 1906.48  2960.8 1904.85  2990.8 1906.23  3068.4 1905.57  3176.3 1904.02
  3925.6 1902.98  4110.2 1903.03    4521 1903.84    4571 1902.71    4721 1904.17
    4841  1902.6    4921 1899.72    4941 1902.37  4984.5 1903.06  4991.3 1902.88
  5003.1 1895.61  5007.6 1893.36  5008.1 1892.86  5020.1 1893.36  5022.4 1897.08
  5032.8 1902.54  5074.4 1901.61  5247.8  1904.8    5272 1907.09    5290 1906.95
  5355.1  1908.3  5373.4 1910.74  5728.2 1915.81  5831.9 1917.97  5967.6 1919.78
#Mann= 12 ,-1 , 0
  2806.4    .035       0  3068.4    .094       0  3176.3    .035       0
  3925.6     .16       0  4110.2    .035       0  5003.1     .16       0
  5007.6    .035       0  5020.1     .16       0  5247.8     .07       0
    5290     .16       0  5728.2     .07       0  5831.9    .035       0
Bank Sta=5007.6,5020.1
XS Rating Curve= 0 ,0
Exp/Cntr=0.3,0.1

Type RM Length L Ch R = 1 ,10988   ,388,388,388
BEGIN DESCRIPTION:
Elm 01 08 10987.78
END DESCRIPTION:
XS GIS Cut Line= 3
       1558055.8      6788091.04      1560121.65      6788068.64
      1561040.17      6787974.54
#Sta/Elev= 30
  2930.4 1906.79  3272.3 1903.66  3401.2 1903.51  3489.6    1903  3509.6 1905.33
  3519.6 1903.54  3549.6    1903  3944.5 1902.87  4162.2 1903.12  4439.6 1902.79
  4574.5 1903.05  4629.7 1902.45  4649.7 1904.58  4699.7 1902.03  4743.3 1902.12
  4899.7 1900.87  4919.7 1899.04  4949.7 1901.06  4969.7 1894.98  4983.5 1893.65
    4984 1893.15    4996 1893.65  5000.6 1897.78  5009.8 1901.45  5019.8  1902.4
  5371.7 1906.65  5616.8 1912.82  5656.5 1913.42    5897    1915  5919.7 1915.18
#Mann= 13 ,-1 , 0
  2930.4    .035       0  3272.3    .063       0  3401.2    .035       0
  3944.5     .16       0  4162.2     .07       0  4439.6    .035       0
  4574.5    .063       0  4743.3    .035       0  4983.5    .035       0
    4996    .035       0  5616.8     .16       0  5656.5    .035       0
    5897     .16       0
Bank Sta=4983.5,4996
XS Rating Curve= 0 ,0
Exp/Cntr=0.3,0.1

Type RM Length L Ch R = 1 ,10600   ,422,422,422
BEGIN DESCRIPTION:
Elm 01 08 10599.79
END DESCRIPTION:
XS GIS Cut Line= 3
      1559073.03      6788489.88      1559897.58      6788373.36
      1560931.35      6788288.34
#Sta/Elev= 30
  4159.2 1902.19    4345 1902.12  4445.4 1902.29  4504.6 1902.85  4656.1 1901.42
  4736.9 1902.24  4776.2 1900.73  4827.7 1900.48  4976.4 1900.88  4991.9 1900.02
  4995.4 1897.53  5000.4 1897.09  5013.2 1892.89  5013.7 1892.39  5025.8 1892.89
  5029.5 1895.99  5039.5 1899.37  5049.6  1900.7  5169.3 1899.81  5310.4 1899.33
  5420.8 1900.94  5445.2 1902.97    5471 1904.27  5521.1 1904.04  5725.8 1907.06
  5792.1 1907.45  5802.1 1908.43  5912.5 1908.06  5982.7 1909.76  6029.2 1907.66
#Mann= 9 ,-1 , 0
  4159.2    .035       0    4345    .063       0  4445.4    .035       0
  4976.4     .16       0  5013.2     .07       0  5025.8     .16       0
  5169.3    .035       0  5445.2     .07       0  5725.8     .16       0
Bank Sta=5013.2,5025.8
XS Rating Curve= 0 ,0
Exp/Cntr=0.3,0.1

Type RM Length L Ch R = 1 ,10178   ,355,355,355
BEGIN DESCRIPTION:
Elm 01 08 10178.19
END DESCRIPTION:
XS GIS Cut Line= 3
       1559158.2      6788624.32      1560023.06      6788722.91
      1561067.24       6788458.5
#Sta/Elev= 30
  4147.4 1901.76    4313  1901.7    4432 1902.61  4795.6 1898.74  4904.6 1899.22
  4959.4 1899.13  4969.5 1896.06  4973.3 1891.86  4973.8 1891.36  4985.9 1891.86
  4999.7 1899.04  5081.8 1899.19  5103.2 1898.52  5112.7 1896.96  5144.2 1897.55
  5164.3 1899.25  5345.6 1899.52  5426.1  1898.5  5606.1 1901.06  5672.1 1903.47
  5707.9 1902.64  5814.2 1904.41  5836.1 1902.75  5865.7 1902.43  5918.1 1905.92
  5962.5 1906.14  6041.1 1907.98  6061.7 1909.73    6080  1909.4    6095 1910.05
#Mann= 11 ,-1 , 0
  4147.4    .035       0    4313    .063       0    4432    .035       0
  4795.6    .063       0  4904.6    .035       0  4973.3    .035       0
  4985.9    .035       0  5345.6     .07       0  5606.1     .16       0
  5962.5    .035       0    6080     .16       0
Bank Sta=4973.3,4985.9
XS Rating Curve= 0 ,0
Exp/Cntr=0.3,0.1

Type RM Length L Ch R = 1 ,9823    ,836,836,836
BEGIN DESCRIPTION:
Elm 01 08 9822.74
END DESCRIPTION:
XS GIS Cut Line= 3
      1559046.15      6788852.87       1560085.8      6789045.56
      1561179.28      6788839.41
#Sta/Elev= 30
  3931.9 1901.38  3952.3  1901.1  4142.9 1901.34  4314.7 1900.87  4835.9 1896.24
  4951.3 1898.79  4979.3 1898.64  5001.5 1890.59    5002 1890.09  5016.1 1890.59
  5017.1 1892.28  5029.1 1895.87  5039.3 1891.33  5055.8 1897.75  5060.9 1894.02
  5108.3 1896.22  5113.3 1892.89  5120.7 1898.62  5137.2 1897.13  5160.7 1892.95
  5181.8 1898.09  5202.1 1893.53  5242.8 1899.27  5339.8 1898.91  5375.1    1900
  5382.4 1896.67  5648.2 1902.96    5846 1903.23  6048.5 1907.84    6102 1910.08
#Mann= 14 ,-1 , 0
  3931.9    .063       0  3952.3    .035       0  4142.9    .063       0
  4314.7    .035       0  4951.3     .16       0  5001.5     .07       0
  5016.1     .16       0  5017.1    .035       0  5137.2     .16       0
  5339.8     .07       0  5382.4     .16       0  5648.2     .07       0
    5846    .035       0  6048.5     .07       0
Bank Sta=5001.5,5016.1
XS Rating Curve= 0 ,0
Exp/Cntr=0.3,0.1

Type RM Length L Ch R = 1 ,8987    ,263,263,263
BEGIN DESCRIPTION:
Elm 01 08 9008.24
END DESCRIPTION:
XS GIS Cut Line= 4
      1558947.57      6789928.38      1559722.81       6789923.9
      1560508.78      6789516.34      1561300.13      6789672.93
#Sta/Elev= 30
  3545.2 1901.17  3772.6 1899.67  4039.3 1897.76  4200.8 1895.67  4272.6 1894.88
    4319 1891.69  4386.2  1895.5    4466 1895.96    4624 1895.52  4651.7 1892.48
  4683.4 1895.28  4883.9 1894.82    4978  1897.3  4994.5 1894.63  5002.7 1888.08
  5003.2 1887.58  5017.3 1888.08  5022.2 1891.72  5038.7 1895.77  5055.1 1891.66
  5066.6 1895.69  5099.5 1892.51  5263.1 1902.01  5507.8 1907.28  5528.2  1905.5
  5619.9 1910.55  5756.4 1913.12  5802.6 1911.82  5915.5 1916.18  6012.5 1915.66
#Mann= 8 ,-1 , 0
  3545.2    .063       0  3772.6    .035       0  4039.3     .16       0
  4200.8    .035       0    4466     .16       0  5002.7     .07       0
  5017.3     .16       0  5066.6     .07       0
Bank Sta=5002.7,5017.3
XS Rating Curve= 0 ,0
Exp/Cntr=0.3,0.1