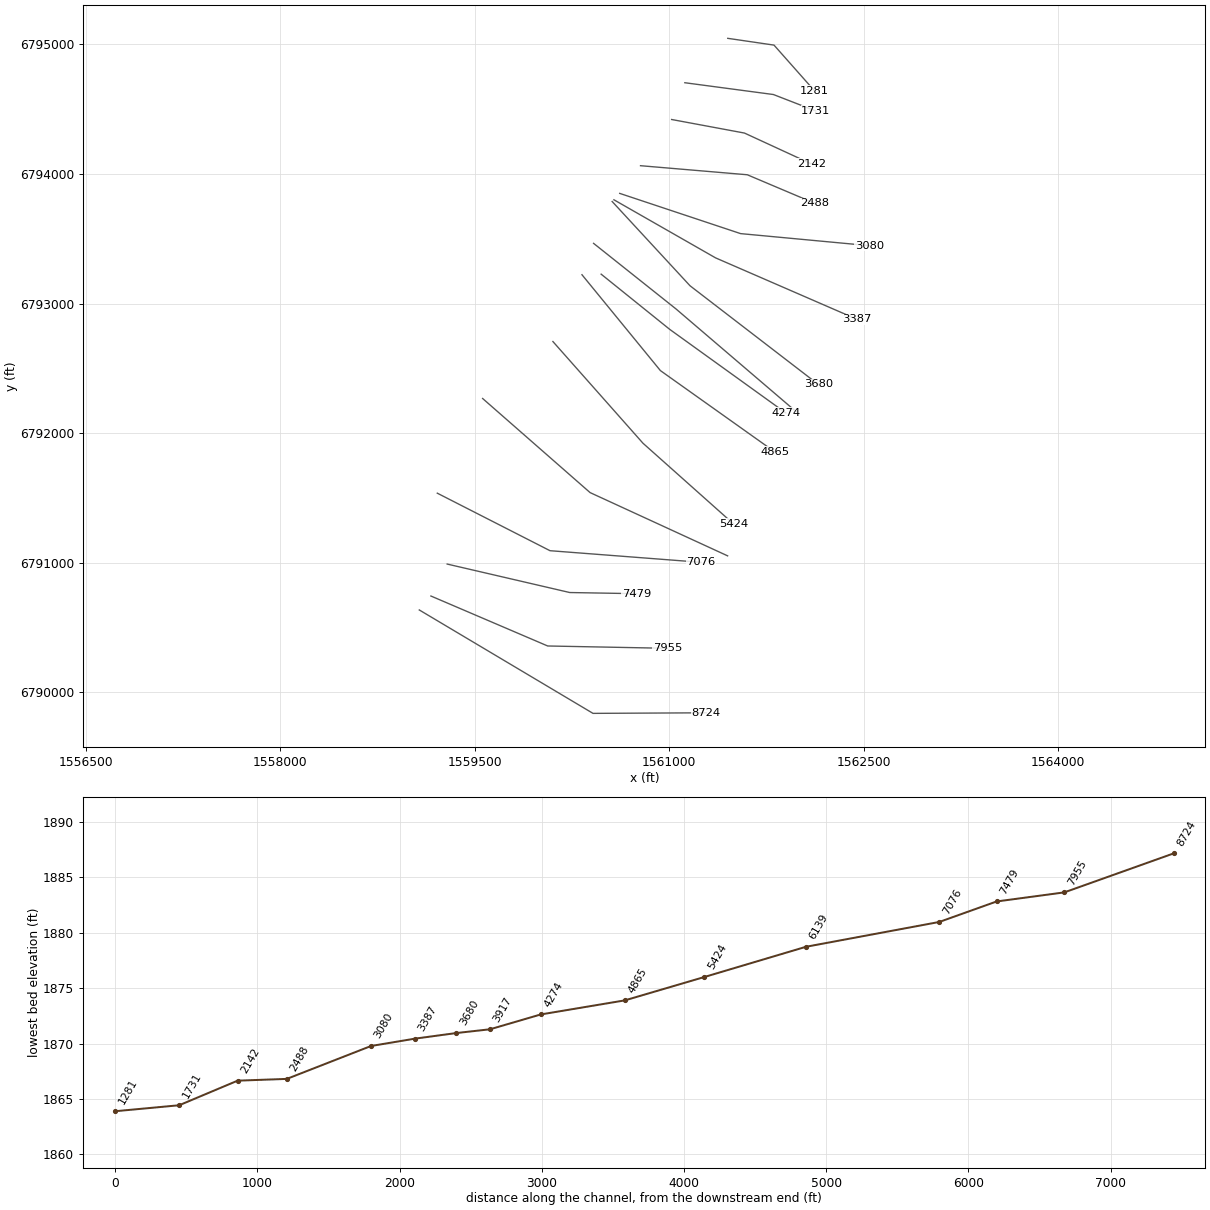
HEC-RAS study Elm 01 08.prj: Elm 01 08 Base Level Engineering

--- Elm 01 08.g01 (geometry) --- (continued)

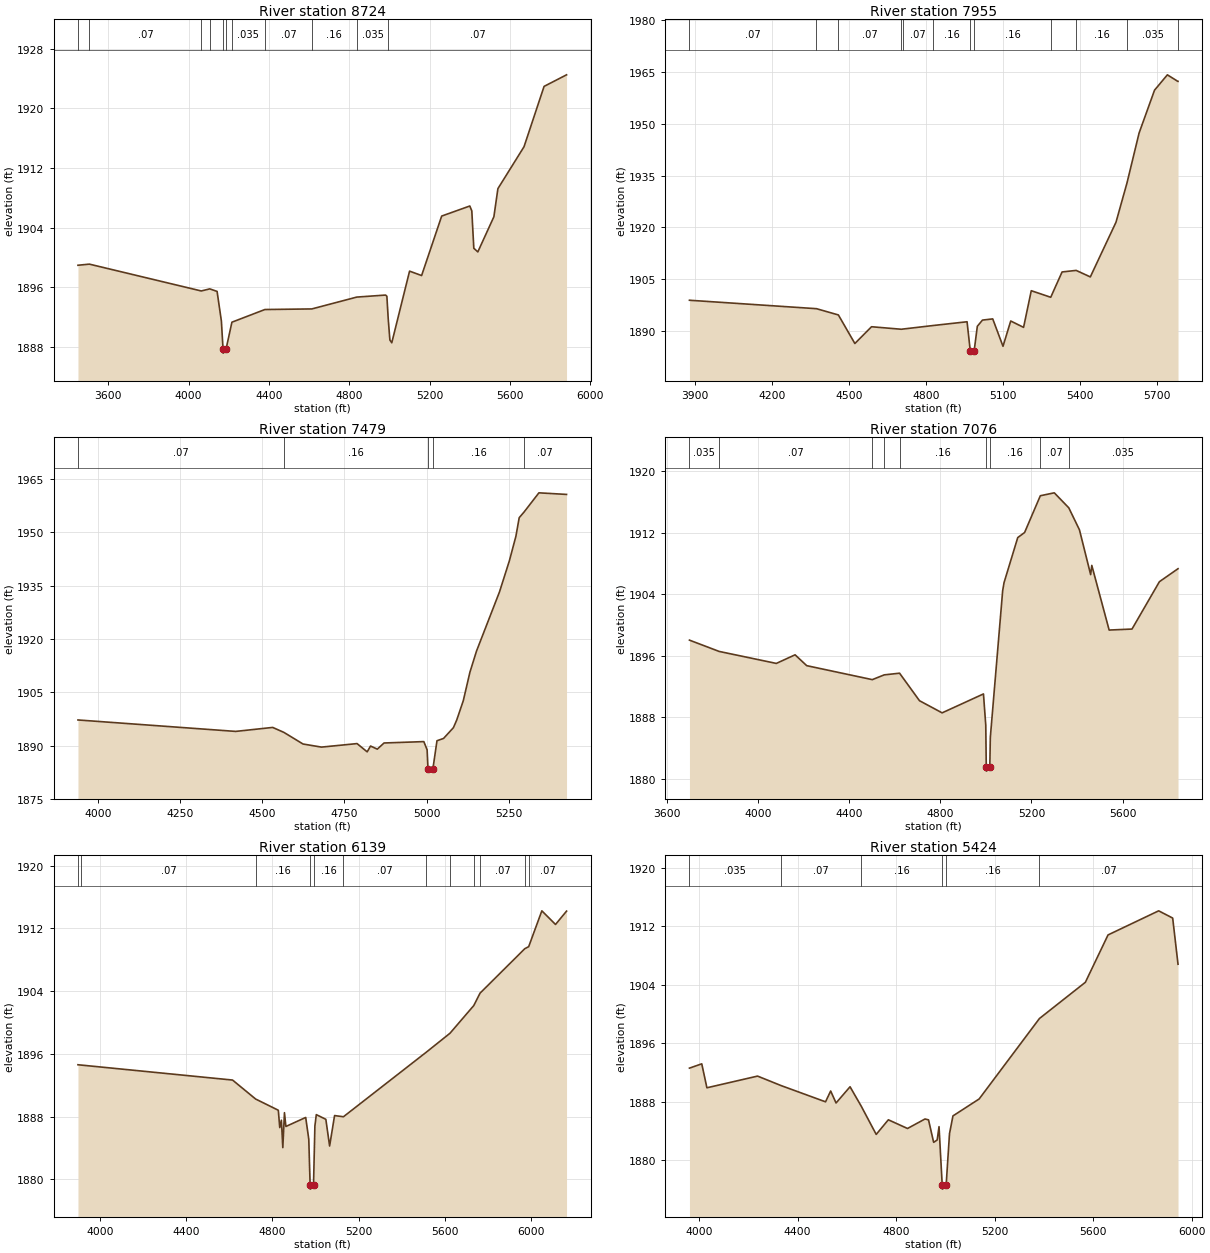
Type RM Length L Ch R = 1 ,8724    ,769,769,769
BEGIN DESCRIPTION:
Elm 01 08 8724.06
END DESCRIPTION:
XS GIS Cut Line= 3
      1559072.99      6790636.44      1560412.93      6789838.75
      1561286.82      6789843.23
#Sta/Elev= 30
  3448.8 1898.96  3505.6 1899.11    4063 1895.51  4105.1 1895.79  4141.7 1895.45
  4163.1 1891.47  4171.4 1887.67  4171.9 1887.17    4186 1887.67  4215.5 1891.32
  4379.7 1893.02  4613.6  1893.1  4837.5 1894.69  4980.9 1894.96  4987.3  1894.8
  4993.9 1891.82  5002.3 1888.93  5011.7 1888.56  5100.3 1898.17  5160.3 1897.58
  5260.3 1905.56  5400.3 1906.91  5410.3 1906.26  5420.3 1901.24  5440.3 1900.75
  5520.3 1905.47  5540.3 1909.24  5670.3 1914.86  5770.3 1922.96  5882.1 1924.51
#Mann= 11 ,-1 , 0
  3448.8    .035       0  3505.6     .07       0    4063    .035       0
  4105.1     .07       0  4171.4     .07       0    4186     .07       0
  4215.5    .035       0  4379.7     .07       0  4613.6     .16       0
  4837.5    .035       0  4993.9     .07       0
Bank Sta=4171.4,4186
XS Rating Curve= 0 ,0
Exp/Cntr=0.3,0.1

Type RM Length L Ch R = 1 ,7955    ,476,476,476
BEGIN DESCRIPTION:
Elm 01 08 7955.4
END DESCRIPTION:
XS GIS Cut Line= 3
      1559162.68      6790743.96      1560063.39      6790358.59
      1560986.53      6790340.66
#Sta/Elev= 30
  3879.1 1898.94  4373.8  1896.5  4459.2 1894.69  4523.4 1886.43  4588.3 1891.28
  4704.9 1890.55  4710.4 1890.61  4829.2 1891.64  4960.4 1892.72  4973.1 1884.15
  4973.6 1883.65  4987.8 1884.15  5000.4 1891.41  5020.4  1893.2  5060.4 1893.55
  5100.4 1885.63  5130.5 1892.94  5180.5  1891.1  5210.5  1901.7  5286.3  1899.8
  5330.5 1907.12  5385.3 1907.57  5440.5 1905.69  5540.5  1921.5  5583.4 1932.88
  5630.5  1947.3  5690.6 1959.68  5740.6 1964.12  5781.5 1962.22  5782.1 1962.22
#Mann= 12 ,-1 , 0
  3879.1     .07       0  4373.8    .035       0  4459.2     .07       0
  4704.9    .035       0  4710.4     .07       0  4829.2     .16       0
  4973.1     .07       0  4987.8     .16       0  5286.3     .07       0
  5385.3     .16       0  5583.4    .035       0  5781.5     .07       0
Bank Sta=4973.1,4987.8
XS Rating Curve= 0 ,0
Exp/Cntr=0.3,0.1

Type RM Length L Ch R = 1 ,7479    ,403,403,403
BEGIN DESCRIPTION:
Elm 01 08 7479.04
END DESCRIPTION:
XS GIS Cut Line= 3
      1559288.14      6790990.45      1560233.68      6790770.87
        1560749.       6790761.9
#Sta/Elev= 30
  3939.5 1897.23  4419.2 1894.01  4531.7 1895.13  4565.6 1893.75  4624.1 1890.46
  4680.2 1889.59  4788.4 1890.58  4819.2 1888.26  4829.4 1889.89    4850 1889.02
  4870.5 1890.75  4991.5 1891.14  5001.5 1888.83  5004.2 1883.33  5004.7 1882.83
  5018.9 1883.33  5031.5 1891.38  5051.5 1892.03  5081.5 1895.06  5091.6 1897.22
  5111.6 1902.67  5131.6 1910.63  5151.6 1916.58  5221.6 1933.26  5251.6 1941.99
  5271.6 1948.94  5281.6 1954.16    5296 1955.71  5341.6 1961.16  5425.6 1960.71
#Mann= 5 ,-1 , 0
  3939.5     .07       0  4565.6     .16       0  5004.2     .07       0
  5018.9     .16       0    5296     .07       0
Bank Sta=5004.2,5018.9
XS Rating Curve= 0 ,0
Exp/Cntr=0.3,0.1

Type RM Length L Ch R = 1 ,7076    ,937,937,937
BEGIN DESCRIPTION:
Elm 01 08 7076.13
END DESCRIPTION:
XS GIS Cut Line= 3
      1559211.95      6791537.17      1560081.31      6791093.52
      1561246.45      6791003.89
#Sta/Elev= 30
  3698.9 1898.02  3829.2 1896.55  4080.2 1894.99  4162.6 1896.11  4213.6  1894.7
  4501.5 1892.88  4553.9  1893.5  4621.2 1893.72  4708.7 1890.14    4808 1888.56
  4989.5 1891.02  4999.6 1886.94  5001.8 1881.48  5002.3 1880.98  5017.3 1881.48
  5019.6 1885.37  5073.8 1904.45  5079.8  1905.5    5140 1911.36  5170.1 1912.02
  5239.1  1916.8  5300.4 1917.18    5364 1915.23  5410.8 1912.37    5460 1906.54
    5465 1907.74  5541.2 1899.33  5641.5 1899.46  5761.8 1905.62  5843.5 1907.31
#Mann= 9 ,-1 , 0
  3698.9    .035       0  3829.2     .07       0  4501.5     .16       0
  4553.9     .07       0  4621.2     .16       0  5001.8     .07       0
  5017.3     .16       0  5239.1     .07       0    5364    .035       0
Bank Sta=5001.8,5017.3
XS Rating Curve= 0 ,0
Exp/Cntr=0.3,0.1

Type RM Length L Ch R = 1 ,6139    ,715,715,715
BEGIN DESCRIPTION:
Elm 01 08 6139.12
END DESCRIPTION:
XS GIS Cut Line= 3
      1559561.47      6792267.64      1560390.53      6791541.65
      1561451.31      6791053.78
#Sta/Elev= 30
  3896.5  1894.6  3911.3 1894.56  4614.6 1892.65  4721.8 1890.23  4827.2  1888.8
  4833.9 1886.59  4841.5 1887.53  4848.1 1884.03  4855.7 1888.49  4862.4 1886.73
  4954.4 1887.88  4968.7 1885.11    4975 1879.24  4975.5 1878.74  4990.7 1879.24
  4997.1 1886.79  5003.7 1888.24    5048 1887.64  5065.5 1884.24  5088.5 1888.12
  5129.7 1887.97  5514.5  1896.2  5624.8 1898.62  5735.2 1902.15  5764.3 1903.73
  5972.2  1909.4  5990.3 1909.66  6051.4 1914.23  6114.9 1912.49  6166.1 1914.19
#Mann= 12 ,-1 , 0
  3896.5    .035       0  3911.3     .07       0  4721.8     .16       0
    4975     .07       0  4990.7     .16       0  5129.7     .07       0
  5514.5     .16       0  5624.8     .07       0  5735.2    .035       0
  5764.3     .07       0  5972.2    .035       0  5990.3     .07       0
Bank Sta=4975,4990.7
XS Rating Curve= 0 ,0
Exp/Cntr=0.3,0.1

Type RM Length L Ch R = 1 ,5424    ,559,559,559
BEGIN DESCRIPTION:
Elm 01 08 5423.51
END DESCRIPTION:
XS GIS Cut Line= 3
       1560103.7      6792706.82      1560798.32      6791922.56
      1561497.42      6791299.65
#Sta/Elev= 30
  3960.7 1892.57  4010.7 1893.16  4031.6 1889.88  4237.3 1891.48    4333 1890.18
  4513.3 1887.96  4534.2 1889.44    4556  1887.8  4612.9 1890.02  4658.8 1887.33
  4719.1  1883.5  4768.4  1885.5  4846.2 1884.31  4917.3 1885.61  4931.5 1885.49
  4952.4 1882.41  4966.7 1882.74  4974.2 1884.56  4987.2 1876.51  4987.7 1876.01
    5003 1876.51  5016.7 1883.59  5030.7 1886.03  5137.1 1888.35  5381.9 1899.36
  5568.5 1904.32  5660.5  1910.8  5866.1  1914.1    5923 1913.11  5944.7 1906.79
#Mann= 6 ,-1 , 0
  3960.7    .035       0    4333     .07       0  4658.8     .16       0
  4987.2     .07       0    5003     .16       0  5381.9     .07       0
Bank Sta=4987.2,5003
XS Rating Curve= 0 ,0
Exp/Cntr=0.3,0.1

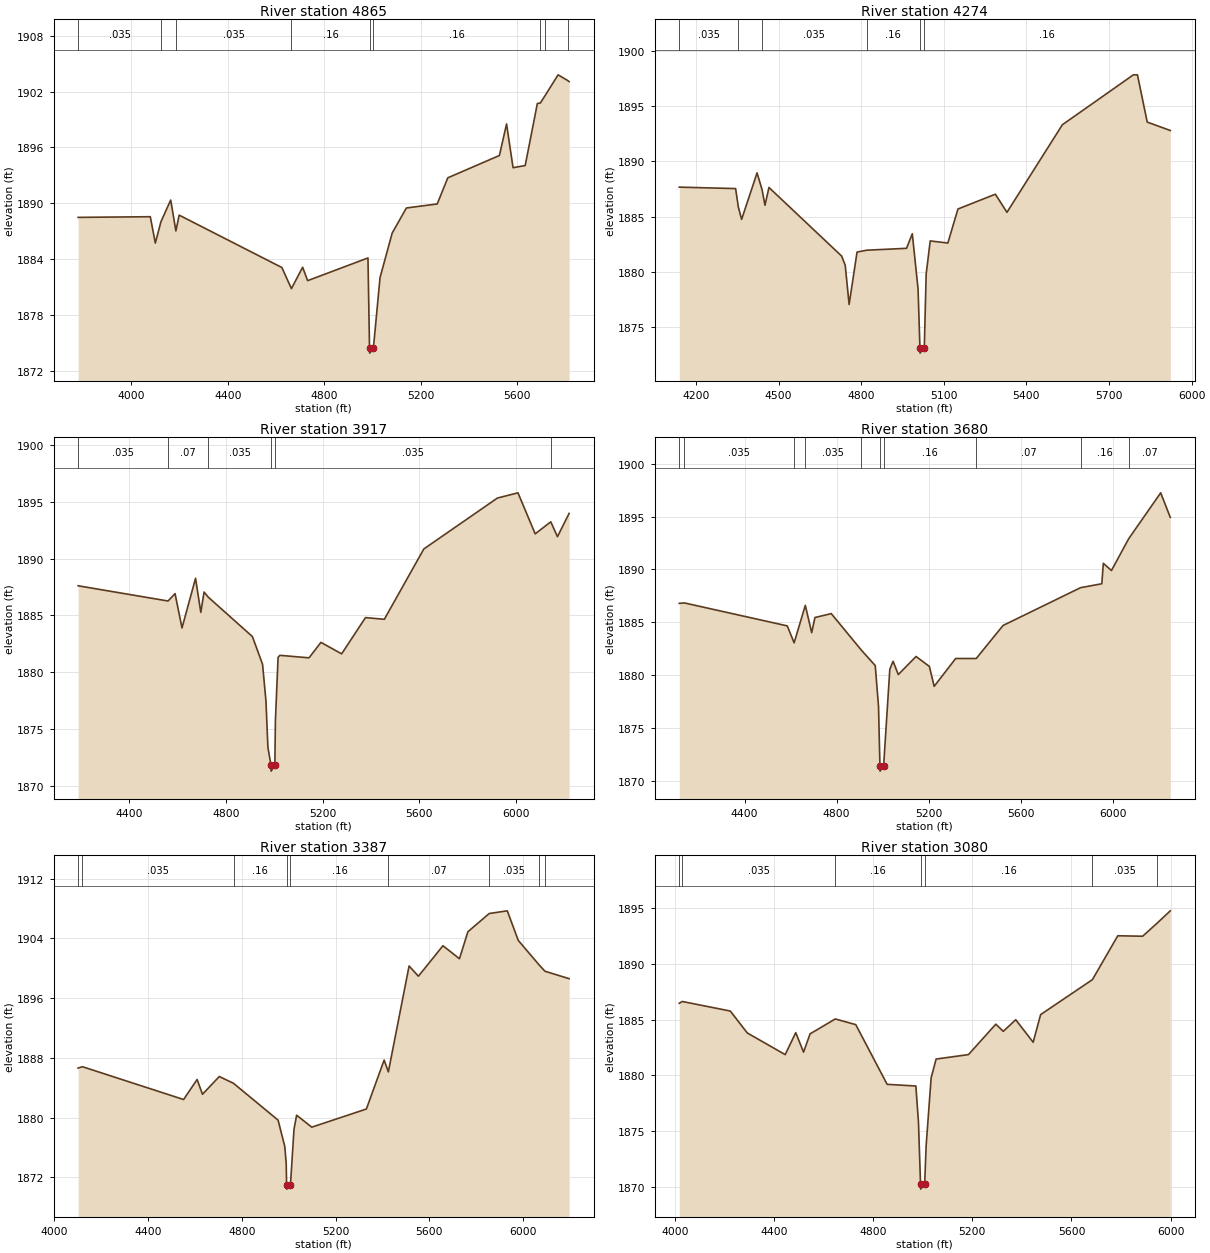
Type RM Length L Ch R = 1 ,4865    ,591,591,591
BEGIN DESCRIPTION:
Elm 01 08 4864.5
END DESCRIPTION:
XS GIS Cut Line= 3
      1560327.82      6793222.11      1560932.76      6792482.73
      1561815.61      6791855.32
#Sta/Elev= 30
  3778.4 1888.49  4078.2 1888.56    4099 1885.73  4122.3 1888.02  4162.9 1890.35
  4184.4 1887.03    4198 1888.73  4624.4  1883.1    4664 1880.83  4710.5 1883.13
  4731.4 1881.69  4981.8 1884.13  4988.3  1874.4  4988.8  1873.9  5004.2  1874.4
  5031.9 1882.02  5082.3  1886.8  5141.3  1889.5  5269.3 1889.93  5313.1 1892.74
  5527.5 1895.14  5557.1 1898.53  5584.1 1893.83  5634.5 1894.06    5685 1900.73
  5697.4 1900.78  5716.2 1901.54  5771.1 1903.81  5811.4 1903.19  5816.8 1903.08
#Mann= 9 ,-1 , 0
  3778.4    .035       0  4122.3     .07       0  4184.4    .035       0
    4664     .16       0  4988.3     .07       0  5004.2     .16       0
  5697.4     .07       0  5716.2     .16       0  5811.4     .07       0
Bank Sta=4988.3,5004.2
XS Rating Curve= 0 ,0
Exp/Cntr=0.3,0.1

Type RM Length L Ch R = 1 ,4274    ,357,357,357
BEGIN DESCRIPTION:
Elm 01 08 4274.36
END DESCRIPTION:
XS GIS Cut Line= 3
       1560475.7       6793226.6      1561004.46       6792800.9
      1561900.38      6792155.84
#Sta/Elev= 30
  4139.6 1887.66  4344.1 1887.53  4354.1 1885.86    4366 1884.74    4422 1888.95
  4440.2 1887.43  4450.8 1886.02  4465.2 1887.63  4729.1 1881.42  4742.1 1880.59
  4756.3 1877.04  4785.1 1881.78  4820.1 1881.95  4964.8 1882.12  4985.7 1883.44
  5006.6 1878.44  5013.4 1873.13  5013.9 1872.63  5029.3 1873.13    5036 1879.78
  5050.7 1882.79  5114.8  1882.6  5151.4 1885.68  5287.3 1887.02  5329.4 1885.38
  5530.6 1893.31  5788.4 1897.83  5803.1 1897.83  5838.7 1893.55  5922.4 1892.79
#Mann= 6 ,-1 , 0
  4139.6    .035       0  4354.1     .07       0  4440.2    .035       0
  4820.1     .16       0  5013.4     .07       0  5029.3     .16       0
Bank Sta=5013.4,5029.3
XS Rating Curve= 0 ,0
Exp/Cntr=0.3,0.1

Type RM Length L Ch R = 1 ,3917    ,237,237,237
BEGIN DESCRIPTION:
Elm 01 08 3916.52
END DESCRIPTION:
XS GIS Cut Line= 3
      1560417.42      6793464.13      1561053.76      6792957.75
      1561980.67      6792165.17
#Sta/Elev= 30
  4187.9  1887.6  4560.3 1886.26  4589.3 1886.91  4618.1 1883.89  4674.2 1888.26
    4696 1885.26  4709.4 1887.05  4726.8  1886.6  4909.6 1883.13  4951.6 1880.69
  4965.7 1877.45  4973.7  1873.4  4986.5 1871.79    4987 1871.29  5002.5 1871.79
  5004.8 1875.76  5015.9  1881.3  5023.2 1881.48  5143.9 1881.26  5193.3 1882.62
    5279 1881.61  5377.7  1884.8  5455.7 1884.65  5619.3 1890.84  5923.8 1895.32
    6009 1895.78  6080.3 1892.17  6144.9 1893.23  6172.5 1891.92  6220.7 1893.97
#Mann= 6 ,-1 , 0
  4187.9    .035       0  4560.3     .07       0  4726.8    .035       0
  4986.5     .07       0  5002.5    .035       0  6144.9     .07       0
Bank Sta=4986.5,5002.5
XS Rating Curve= 0 ,0
Exp/Cntr=0.3,0.1

Type RM Length L Ch R = 1 ,3680    ,293,293,293
BEGIN DESCRIPTION:
Elm 01 08 3680.02
END DESCRIPTION:
XS GIS Cut Line= 3
      1560560.79      6793786.81      1561161.31        6793137.
      1562150.82      6792375.84
#Sta/Elev= 30
  4116.3  1886.8  4138.3 1886.84  4585.5 1884.67  4615.3 1883.07  4663.9 1886.61
  4691.6 1884.03  4705.7 1885.46  4776.6 1885.83  4907.8 1882.37  4967.7 1880.92
  4981.9 1877.08  4988.1 1871.45  4988.6 1870.95  5004.1 1871.45    5031 1880.57
  5045.2 1881.33  5067.9 1880.07  5144.9 1881.78  5202.9 1880.84  5223.7 1878.96
  5317.1 1881.59  5406.4 1881.59    5523 1884.71  5859.8 1888.28    5952 1888.65
  5958.6 1890.58  5993.9  1889.9  6068.7  1892.9  6207.8 1897.24  6249.5 1894.92
#Mann= 10 ,-1 , 0
  4116.3    .045       0  4138.3    .035       0  4615.3     .07       0
  4663.9    .035       0  4907.8     .16       0  4988.1     .07       0
  5004.1     .16       0  5406.4     .07       0  5859.8     .16       0
  6068.7     .07       0
Bank Sta=4988.1,5004.1
XS Rating Curve= 0 ,0
Exp/Cntr=0.3,0.1

Type RM Length L Ch R = 1 ,3387    ,307,307,307
BEGIN DESCRIPTION:
Elm 01 08 3386.53
END DESCRIPTION:
XS GIS Cut Line= 3
      1560574.28      6793800.22      1561358.49       6793352.1
      1562450.94      6792877.51
#Sta/Elev= 30
  4101.6 1886.64  4120.3 1886.82  4551.6 1882.43  4609.2 1885.11  4632.2 1883.13
  4703.9 1885.51  4764.5  1884.6  4954.7 1879.67  4983.2 1876.14  4989.3 1873.85
  4990.9 1870.94  4991.4 1870.44  5007.2 1870.94  5022.5 1878.45  5033.7 1880.33
  5098.3 1878.73  5331.2 1881.16    5407 1887.71    5425 1886.13  5513.4  1900.3
  5553.1 1898.93  5657.9 1903.01  5728.2 1901.27  5764.2 1904.88  5855.1 1907.32
  5932.2 1907.68  5979.1 1903.72  6066.4  1900.5  6092.7  1899.6  6195.9  1898.6
#Mann= 9 ,-1 , 0
  4101.6    .045       0  4120.3    .035       0  4764.5     .16       0
  4990.9     .07       0  5007.2     .16       0    5425     .07       0
  5855.1    .035       0  6066.4     .07       0  6092.7    .035       0
Bank Sta=4990.9,5007.2
XS Rating Curve= 0 ,0
Exp/Cntr=0.3,0.1

Type RM Length L Ch R = 1 ,3080    ,592,592,592
BEGIN DESCRIPTION:
Elm 01 08 2850.764
END DESCRIPTION:
XS GIS Cut Line= 3
      1560619.03      6793849.54      1561551.56      6793539.26
      1562546.02      6793446.21
#Sta/Elev= 30
  4017.2 1886.47  4029.4 1886.63  4223.2 1885.77  4291.8  1883.8  4444.7 1881.86
  4487.2 1883.83  4518.8 1882.08  4544.9 1883.72  4646.8 1885.06  4729.5 1884.55
  4856.1 1879.19    4972 1879.04  4982.5 1875.81  4990.8 1870.28  4991.3 1869.78
  5007.6 1870.28  5013.5 1873.68  5033.6 1879.76  5053.7 1881.46  5184.2 1881.86
  5294.7 1884.59  5324.8 1883.95  5375.1 1884.99  5445.4 1882.97  5475.5 1885.45
  5684.5 1888.59  5786.9 1892.53  5887.3 1892.49  5945.1 1893.65  5998.8 1894.77
#Mann= 7 ,-1 , 0
  4017.2    .045       0  4029.4    .035       0  4646.8     .16       0
  4990.8     .07       0  5007.6     .16       0  5684.5    .035       0
  5945.1     .07       0
Bank Sta=4990.8,5007.6
XS Rating Curve= 0 ,0
Exp/Cntr=0.3,0.1

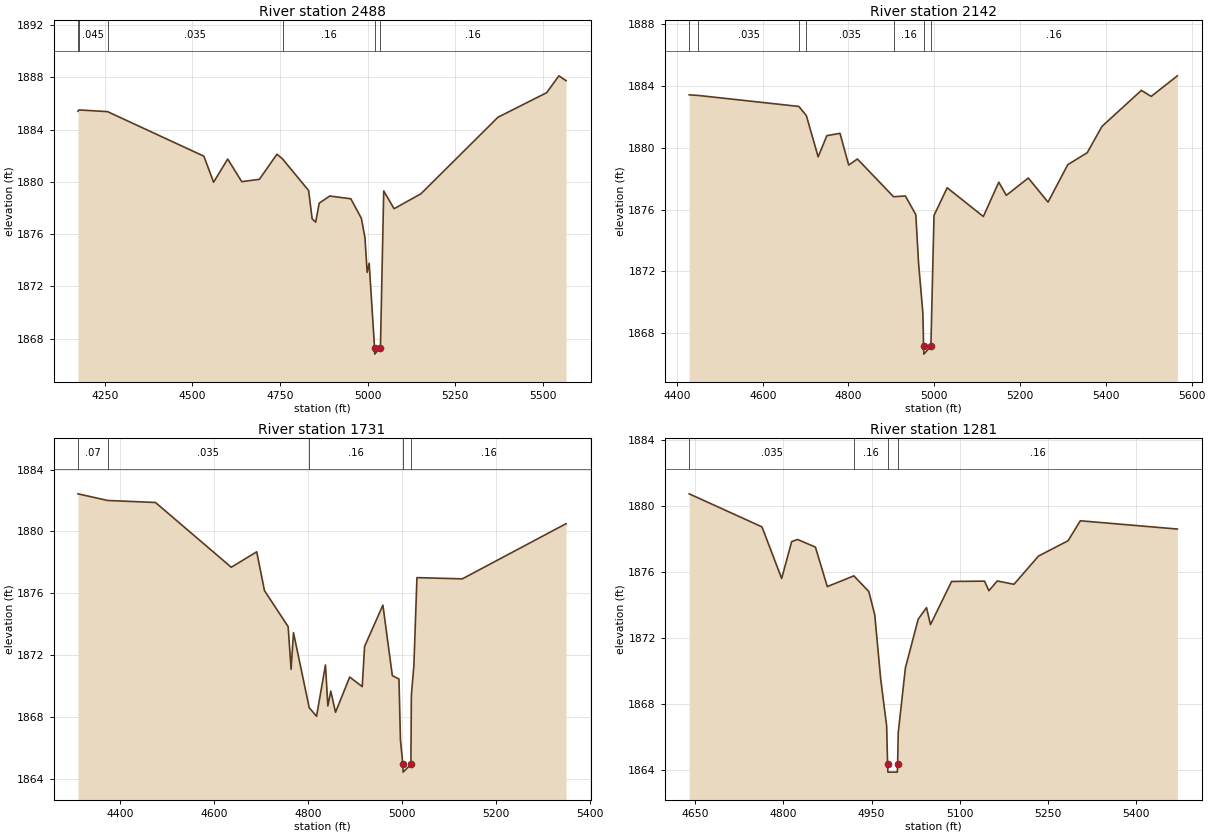
Type RM Length L Ch R = 1 ,2488    ,346,346,346
BEGIN DESCRIPTION:
Elm 01 08 3744
END DESCRIPTION:
XS GIS Cut Line= 3
      1560779.47      6794063.13      1561602.92      6793993.26
      1562123.93      6793772.63
#Sta/Elev= 30
  4173.6  1885.4  4176.6  1885.5    4258 1885.37  4532.7 1881.96  4560.5 1879.97
  4600.7 1881.74  4640.8 1880.01    4691 1880.19  4741.2 1882.11  4757.2 1881.75
  4831.5 1879.33  4841.5 1877.17  4851.6 1876.91  4861.6 1878.36  4891.7 1878.91
  4951.9  1878.7    4982  1877.2  4992.1 1875.73  4998.5 1873.07  5004.2 1873.77
  5019.5 1867.31    5020 1866.81  5036.3 1867.31  5045.7  1879.3  5075.2 1877.94
  5151.7 1879.08  5371.5 1884.94  5510.4 1886.82  5545.2 1888.11  5565.8 1887.74
#Mann= 6 ,-1 , 0
  4173.6     .07       0  4176.6    .045       0    4258    .035       0
  4757.2     .16       0  5019.5     .07       0  5036.3     .16       0
Bank Sta=5019.5,5036.3
XS Rating Curve= 0 ,0
Exp/Cntr=0.3,0.1

Type RM Length L Ch R = 1 ,2142    ,411,411,411
BEGIN DESCRIPTION:
Elm 01 08 3746
END DESCRIPTION:
XS GIS Cut Line= 3
      1561019.47      6794419.47      1561581.13      6794314.93
      1562095.77      6794077.67
#Sta/Elev= 30
  4428.7 1883.42  4450.2 1883.38  4684.3 1882.67  4701.8 1882.08  4729.3 1879.41
  4749.6 1880.78  4780.2 1880.93  4800.5 1878.88  4820.8 1879.27  4905.1 1876.83
  4932.7 1876.88    4957 1875.67  4963.3 1872.56  4973.4 1869.32  4975.1 1867.15
  4975.6 1866.65  4992.1 1867.15  4999.4 1875.62  5030.1 1877.41  5114.4 1875.55
  5150.4 1877.77  5167.9 1876.92  5219.3 1878.04  5265.2 1876.48  5311.1  1878.9
  5356.6 1879.68    5391 1881.38  5482.8 1883.71  5505.7 1883.32  5566.7 1884.65
#Mann= 7 ,-1 , 0
  4428.7     .07       0  4450.2    .035       0  4684.3     .07       0
  4701.8    .035       0  4905.1     .16       0  4975.1     .07       0
  4992.1     .16       0
Bank Sta=4975.1,4992.1
XS Rating Curve= 0 ,0
Exp/Cntr=0.3,0.1

Type RM Length L Ch R = 1 ,1731    ,450,450,450
BEGIN DESCRIPTION:
Elm 01 08 3750
END DESCRIPTION:
XS GIS Cut Line= 3
      1561121.32      6794703.08      1561804.23      6794612.16
      1562131.05      6794485.33
#Sta/Elev= 30
  4309.6 1882.43  4372.8    1882  4474.7 1881.87  4636.1 1877.68  4690.3 1878.68
  4706.8 1876.17  4757.2 1873.84  4763.5 1871.08  4768.6 1873.45  4802.1  1868.6
  4817.7 1868.04  4836.7 1871.36  4841.8 1868.71    4848 1869.67  4858.1  1868.3
  4888.3 1870.58    4915 1869.96    4920 1872.56    4959 1875.23  4979.1 1870.67
  4993.2 1870.45  4996.4 1866.49  5001.5 1864.93    5002 1864.43  5018.6 1864.93
  5019.6  1869.4    5025 1871.34  5031.5 1877.01  5128.1 1876.93  5349.1  1880.5
#Mann= 5 ,-1 , 0
  4309.6     .07       0  4372.8    .035       0  4802.1     .16       0
  5001.5     .07       0  5018.6     .16       0
Bank Sta=5001.5,5018.6
XS Rating Curve= 0 ,0
Exp/Cntr=0.3,0.1

Type RM Length L Ch R = 1 ,1281    ,322,322,322
BEGIN DESCRIPTION:
Elm 01 08 3752
END DESCRIPTION:
XS GIS Cut Line= 3
      1561452.43      6795045.53      1561809.03       6794993.3
      1562121.13      6794641.09
#Sta/Elev= 30
  4639.6 1880.72  4763.5 1878.72    4797  1875.6    4814 1877.83  4824.1 1877.96
  4854.4  1877.5  4874.7 1875.11  4919.9 1875.76  4945.4 1874.81  4955.5 1873.39
  4965.6 1869.51  4975.7 1866.69  4977.3 1864.39  4977.8 1863.89  4993.9 1863.89
  4994.4 1864.39  4995.4 1866.26  5007.6 1870.19  5029.4 1873.14  5043.6 1873.84
  5050.3 1872.81  5086.3 1875.42  5142.3 1875.44  5149.8 1874.86    5164 1875.45
  5192.5 1875.25  5234.3 1876.96  5284.5 1877.88  5305.4 1879.09  5470.6 1878.59
#Mann= 4 ,-1 , 0
  4639.6    .035       0  4919.9     .16       0  4977.3     .07       0
  4994.4     .16       0
Bank Sta=4977.3,4994.4
XS Rating Curve= 0 ,0
Exp/Cntr=0.3,0.1