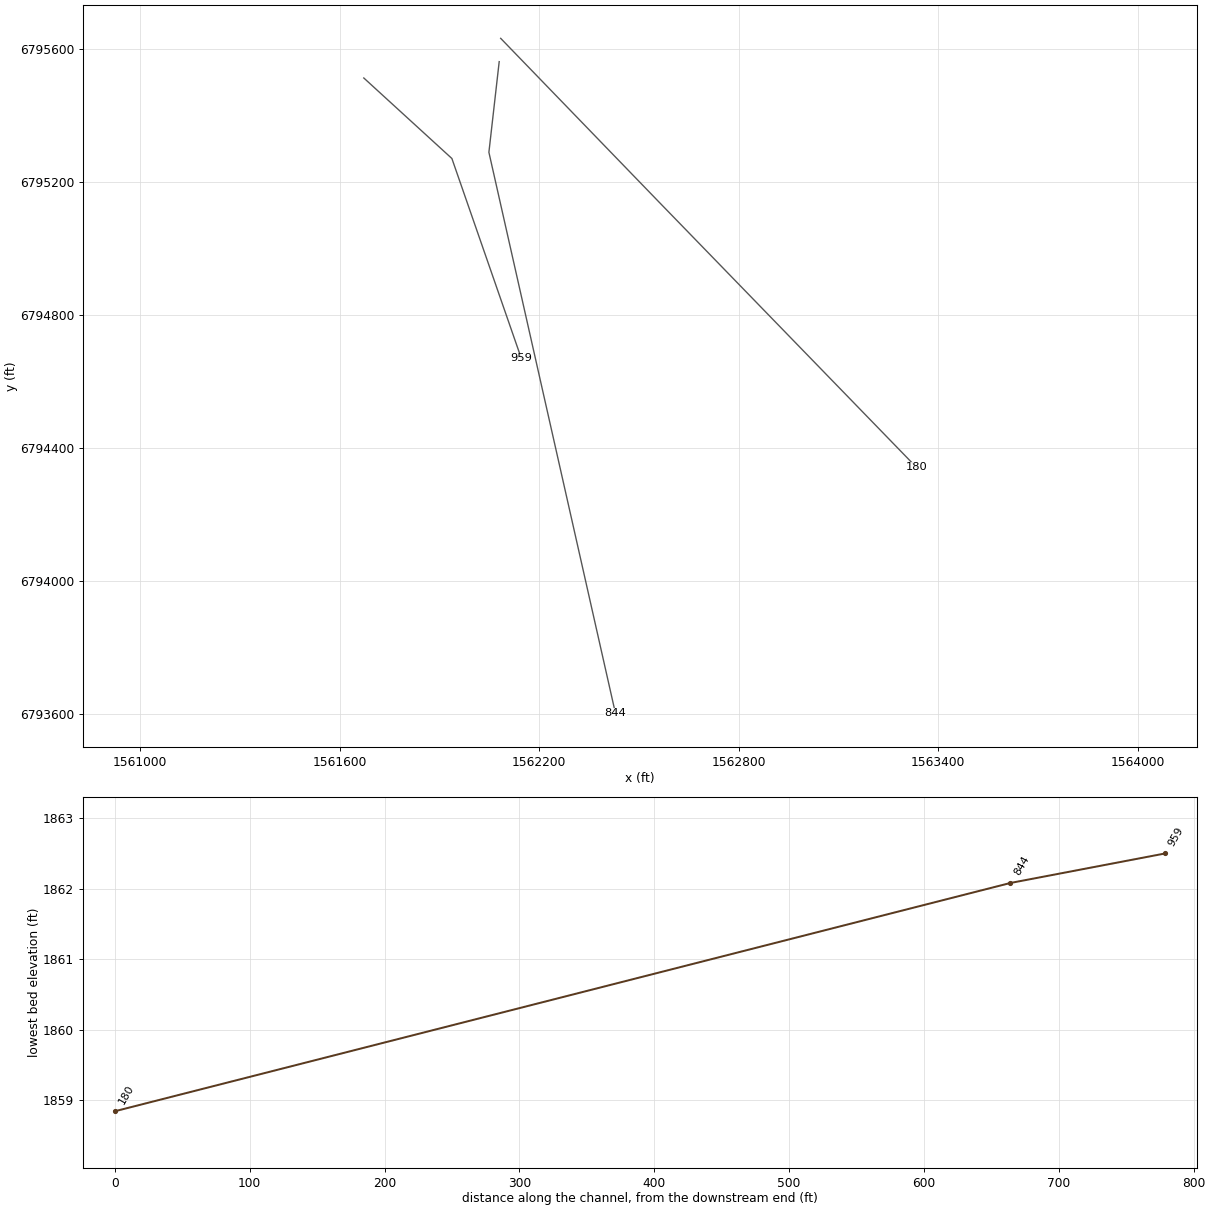
HEC-RAS study Elm 01 08.prj: Elm 01 08 Base Level Engineering

--- Elm 01 08.g01 (geometry) --- (continued)

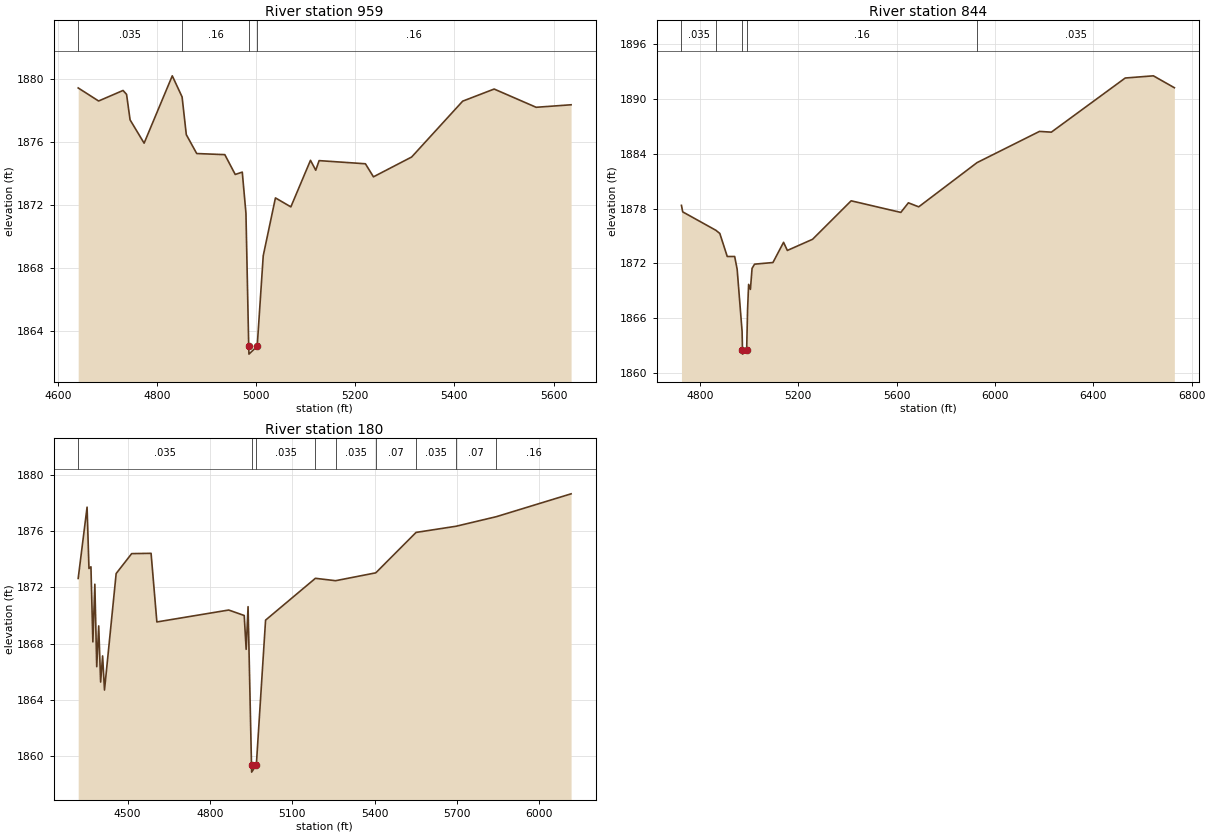
Type RM Length L Ch R = 1 ,959     ,115,115,115
BEGIN DESCRIPTION:
Elm 01 08 3755
END DESCRIPTION:
XS GIS Cut Line= 3
      1561673.01      6795513.86      1561937.79      6795271.73
      1562146.22      6794671.38
#Sta/Elev= 30
  4641.2 1879.42  4682.4 1878.59  4731.7 1879.26  4738.8 1879.01  4745.9 1877.39
  4774.2 1875.91    4831 1880.19  4850.8 1878.85  4859.3 1876.45  4880.3 1875.25
    4937 1875.18    4958 1873.92  4972.2 1874.07  4979.6 1871.46  4985.2    1863
  4985.7  1862.5  5002.3    1863  5014.5 1868.76  5039.1 1872.43  5070.2 1871.86
  5109.8 1874.82  5120.4 1874.19  5127.2  1874.8  5220.6  1874.6  5236.8 1873.77
  5313.9 1875.03  5416.8 1878.58  5480.3 1879.35    5565 1878.19  5635.5 1878.35
#Mann= 4 ,-1 , 0
  4641.2    .035       0  4850.8     .16       0  4985.2     .07       0
  5002.3     .16       0
Bank Sta=4985.2,5002.3
XS Rating Curve= 0 ,0
Exp/Cntr=0.3,0.1

Type RM Length L Ch R = 1 ,844     ,664,664,664
BEGIN DESCRIPTION:
Elm 01 08 3685
END DESCRIPTION:
XS GIS Cut Line= 3
        1562080.      6795563.03      1562049.03      6795290.39
      1562429.52      6793603.05
#Sta/Elev= 30
  4725.6 1878.35  4730.7 1877.64  4865.3 1875.63  4881.6 1875.28  4911.8 1872.76
    4942 1872.76  4952.1 1871.36  4972.2 1864.56  4973.7 1862.58  4974.2 1862.08
  4990.8 1862.58  4994.4  1866.9  4998.7 1869.71    5006 1869.16  5012.7 1871.46
  5022.9 1871.92  5097.6  1872.1  5140.8 1874.31  5156.2 1873.42  5258.7 1874.64
  5415.6 1878.85  5617.5 1877.58  5648.3 1878.63  5690.3 1878.19  5927.6 1883.03
  6181.3 1886.44  6229.6 1886.36  6529.9 1892.28  6644.4 1892.52  6729.7 1891.22
#Mann= 5 ,-1 , 0
  4725.6    .035       0  4865.3     .16       0  4973.7     .07       0
  4990.8     .16       0  5927.6    .035       0
Bank Sta=4973.7,4990.8
XS Rating Curve= 0 ,0
Exp/Cntr=0.3,0.1

Type RM Length L Ch R = 1 ,180     ,0,0,0
BEGIN DESCRIPTION:
Elm 01 08 3682
END DESCRIPTION:
XS GIS Cut Line= 3
      1562084.44      6795633.12       1562557.2      6795144.07
       1563334.5      6794342.73
#Sta/Elev= 30
  4319.8 1872.64  4352.2 1877.72  4359.1 1873.35  4366.3 1873.47  4373.3 1868.12
  4380.5 1872.23  4387.4 1866.35  4394.6 1869.26  4401.6 1865.26  4408.8 1867.12
  4415.7 1864.69  4458.2 1872.99  4514.8 1874.41  4585.5 1874.43  4606.6 1869.54
  4868.5 1870.39    4925    1870    4932 1867.59    4939 1870.63  4951.5 1859.34
    4952 1858.84  4969.1 1859.34  5002.8 1869.67  5184.4 1872.65  5258.1 1872.48
  5404.5 1873.04  5551.3 1875.92  5697.2 1876.36  5843.6 1877.04  6116.4 1878.67
#Mann= 9 ,-1 , 0
  4319.8    .035       0  4951.5    .035       0  4969.1    .035       0
  5184.4     .07       0  5258.1    .035       0  5404.5     .07       0
  5551.3    .035       0  5697.2     .07       0  5843.6     .16       0
Bank Sta=4951.5,4969.1
XS Rating Curve= 0 ,0
Exp/Cntr=0.3,0.1

Chan Stop Cuts=-1
Use User Specified Reach Order=0
Composite Channel Slope=5