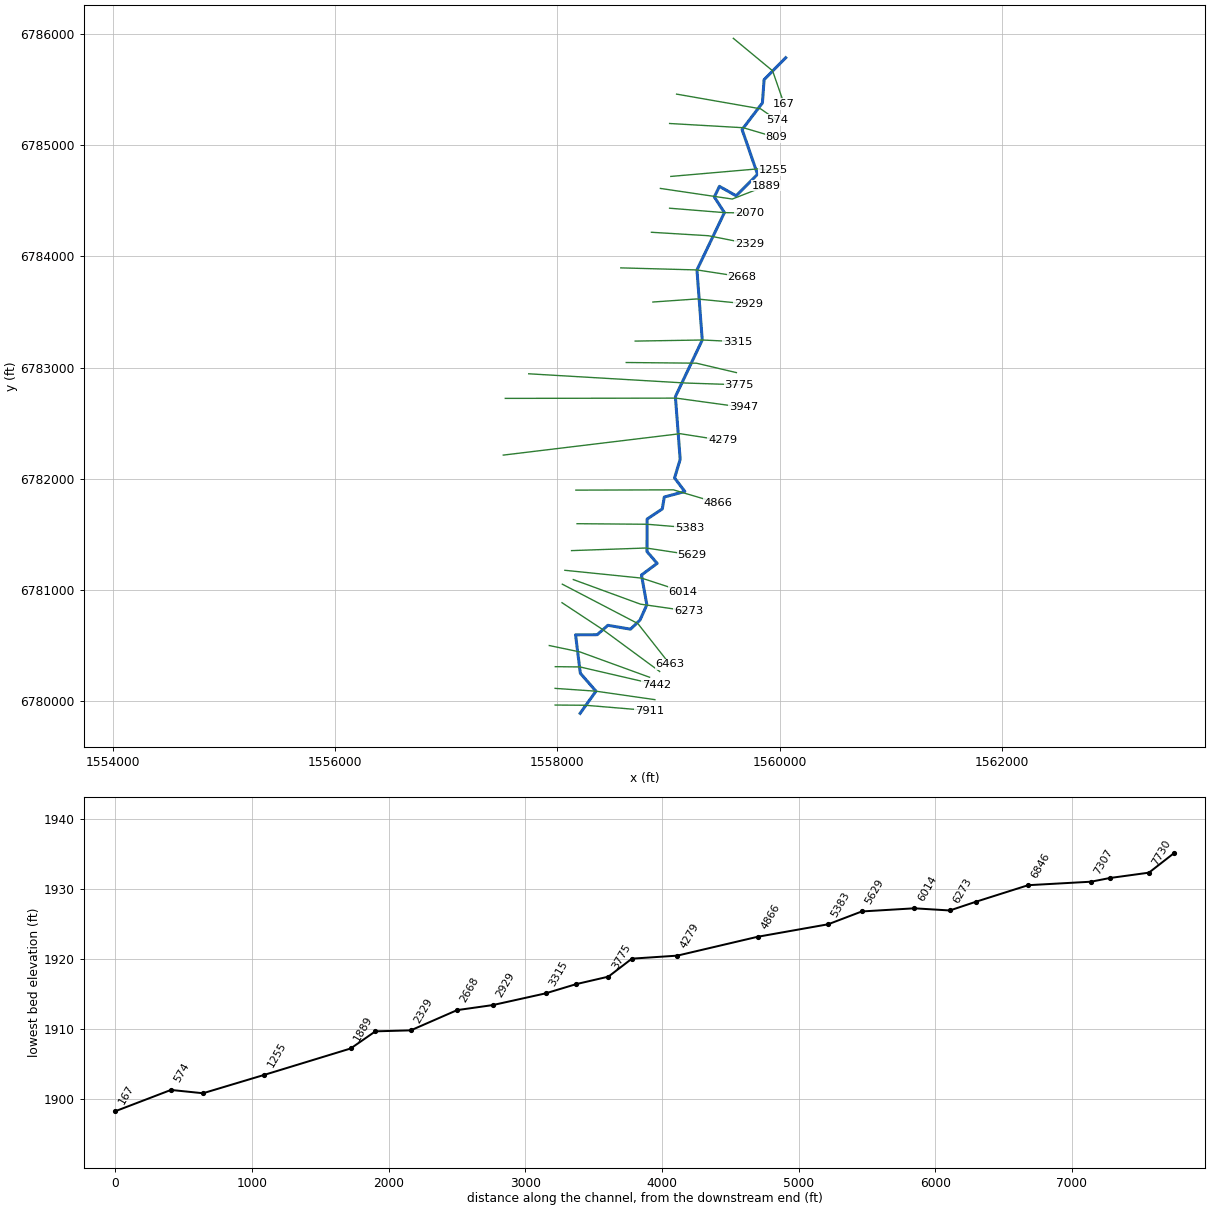
--- Elm 01 09.prj (project) ---

Proj Title=Elm 01 09 Base Level Engineering
Current Plan=p01
Default Exp/Contr=0.3,0.1
English Units
Geom File=g01
Flow File=f01
Plan File=p01
BEGIN DESCRIPTION:
Elm 01 09
END DESCRIPTION:

--- Elm 01 09.p01 (plan) ---

Plan Title=Multiple Run
Short Identifier=Multiple
Geom File=g01
Flow File=f01
Subcritical Flow
K Sum by GR= 0
Std Step Tol= 0.01
Critical Tol= 0.01
Num of Std Step Trials= 20
Max Error Tol= 0.3
Flow Tol Ratio= 0.001
Split Flow NTrial= 30
Split Flow Tol= 0.02
Split Flow Ratio= 0.02
Log Output Level= 0
Friction Slope Method= 1
Unsteady Friction Slope Method= 2
Unsteady Bridges Friction Slope Method= 1
Parabolic Critical Depth
Global Vel Dist=  1 , 1 , 1
Global Log Level= 0
CheckData=True
Encroach Param= -1, 0, 0, 0
BEGIN DESCRIPTION:
Multiple Run
END DESCRIPTION:

--- Elm 01 09.f01 (steady flow) ---

Flow Title=Multiple
Number of Profiles=7
Profile Names=10-year,25-year,50-year,1pct_min,100-year,1pct_plu,500-year
River Rch & RM= Elm 01 09,Reach-1,7911
     222     303     369     279     447     615     665
River Rch & RM= Elm 01 09,Reach-1,6463
     341     477     590     452     724     996    1100
Boundary for River Rch & Prof#=Elm 01 09,Reach-1,1
Up Type=0
Dn Type=3
Dn Slope=0.005
Boundary for River Rch & Prof#=Elm 01 09,Reach-1,2
Up Type=0
Dn Type=3
Dn Slope=0.005
Boundary for River Rch & Prof#=Elm 01 09,Reach-1,3
Up Type=0
Dn Type=3
Dn Slope=0.005
Boundary for River Rch & Prof#=Elm 01 09,Reach-1,4
Up Type=0
Dn Type=3
Dn Slope=0.005
Boundary for River Rch & Prof#=Elm 01 09,Reach-1,5
Up Type=0
Dn Type=3
Dn Slope=0.005
Boundary for River Rch & Prof#=Elm 01 09,Reach-1,6
Up Type=0
Dn Type=3
Dn Slope=0.005
Boundary for River Rch & Prof#=Elm 01 09,Reach-1,7
Up Type=0
Dn Type=3
Dn Slope=0.005

--- Elm 01 09.g01 (geometry) ---

Geom Title=Existing Conditions

River Reach=Elm 01 09,Reach-1
Reach XY= 30
      1558205.00      6779888.00      1558347.77      6780087.71
      1558206.87      6780249.15      1558163.99      6780595.07
      1558358.42      6780595.83      1558455.00      6780680.43
      1558658.42      6780645.81      1558744.24      6780728.27
      1558805.51      6780865.24      1558757.08      6781132.74
      1558898.00      6781237.78      1558806.98      6781343.89
      1558808.04      6781636.58      1558944.59      6781727.94
      1558962.68      6781834.89      1559147.52      6781884.38
      1559054.94      6782006.28      1559105.44      6782174.18
      1559062.33      6782738.10      1559304.07      6783247.85
      1559256.38      6783878.34      1559503.41      6784394.05
      1559412.78      6784534.62      1559458.63      6784630.59
      1559608.58      6784545.50      1559801.63      6784739.28
      1559662.62      6785141.33      1559845.43      6785381.41
      1559860.52      6785590.43      1560055.00      6785788.00

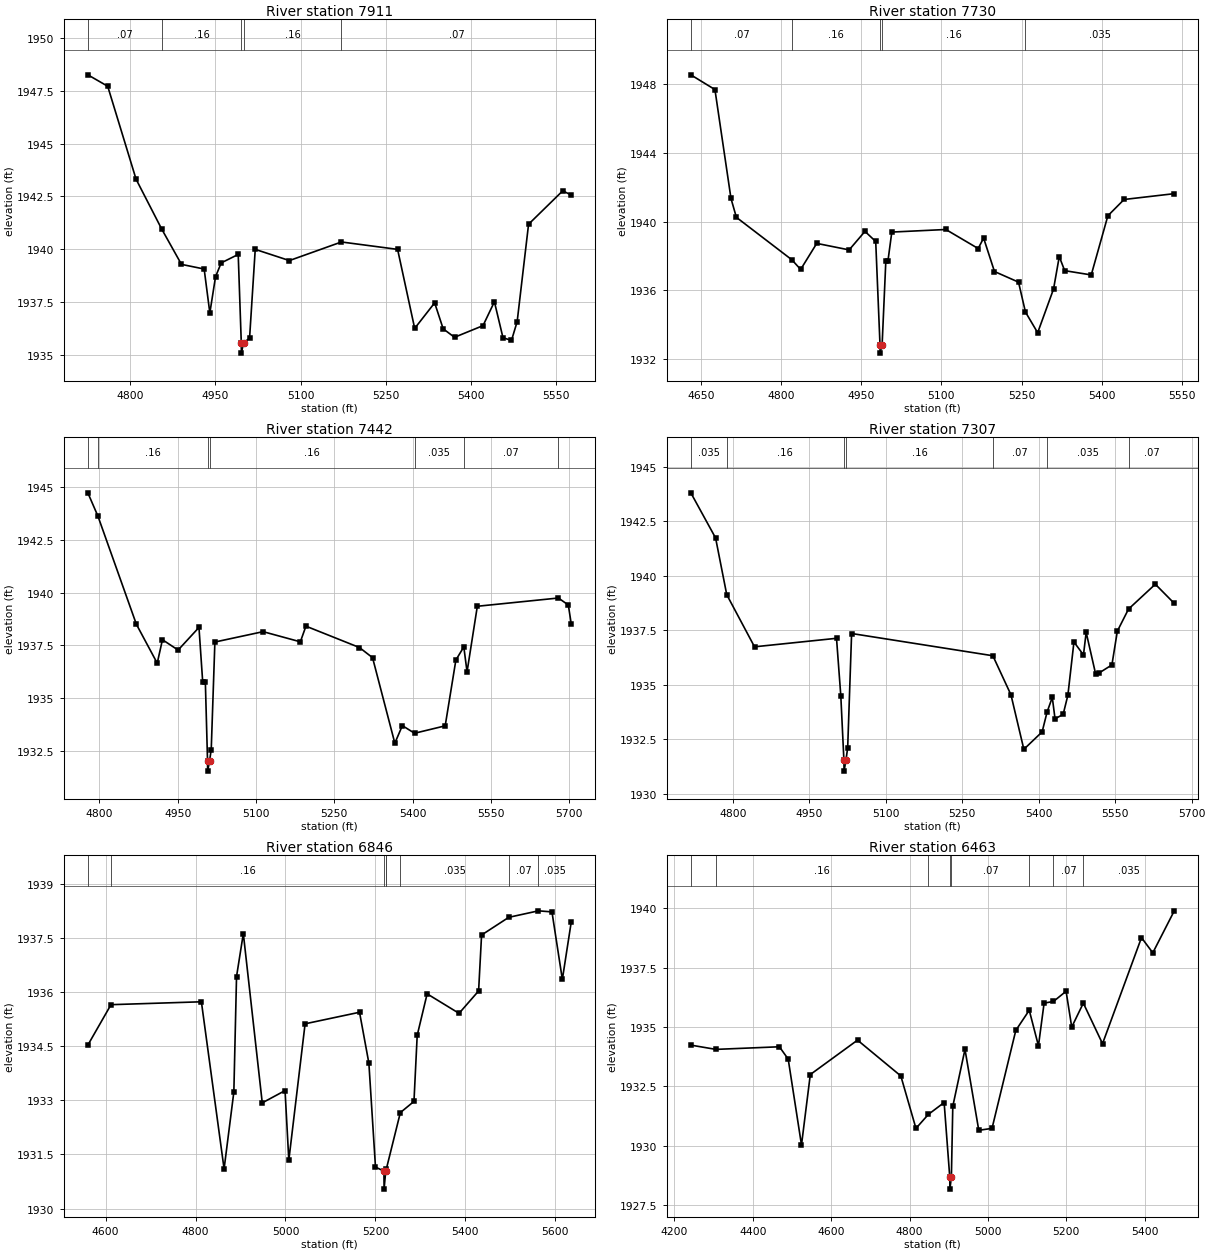
Type RM Length L Ch R = 1,7911,181,181,181
BEGIN DESCRIPTION:
Elm 01 09 3760
END DESCRIPTION:
XS GIS Cut Line= 3
      1557980.05      6779963.00      1558254.84      6779960.96
      1558830.04      6779913.00
#Sta/Elev= 30
  4725.2 1948.25  4760.2 1947.71  4810.2 1943.31  4855.2 1940.96  4890.2 1939.28
  4930.2 1939.06  4940.2 1936.98  4950.2 1938.69  4960.2 1939.35  4990.2 1939.75
  4995.6 1935.58  4995.8 1935.08  4999.6 1935.58  5010.2 1935.78  5020.2 1939.99
  5080.4 1939.46  5172.1 1940.34  5271.1 1939.99  5301.2 1936.25  5336.4 1937.46
  5351.4 1936.23  5371.4 1935.83  5421.6 1936.38  5441.7 1937.51  5456.8 1935.81
  5471.8 1935.68  5481.8 1936.57  5501.9 1941.18  5562.1 1942.76  5577.2 1942.56
#Mann=5,-1,0
  4725.2    0.07       0  4855.2    0.16       0  4995.6    0.07       0
  4999.6    0.16       0  5172.1    0.07       0
Bank Sta=4995.6,4999.6
Exp/Cntr=0.3,0.1

Type RM Length L Ch R = 1,7730,288,288,288
BEGIN DESCRIPTION:
Elm 01 09 3757
END DESCRIPTION:
XS GIS Cut Line= 3
      1557980.04      6780113.00      1558347.77      6780087.71
      1558877.92      6780011.50
#Sta/Elev= 30
  4631.4 1948.56  4676.5 1947.70  4706.5 1941.35  4716.6 1940.25  4820.5 1937.77
  4836.8 1937.21  4866.9 1938.73  4927.5 1938.35  4957.1 1939.43  4977.2 1938.84
  4985.2 1932.83  4985.4 1932.33  4989.2 1932.83  4996.1 1937.69  5000.0 1937.69
  5007.3 1939.39  5108.4 1939.54  5168.8 1938.43  5179.0 1939.04  5199.3 1937.09
  5244.3 1936.47  5257.2 1934.73  5280.1 1933.52  5309.8 1936.07  5320.5 1937.96
  5330.6 1937.14  5380.3 1936.89  5411.4 1940.34  5441.7 1941.29  5535.6 1941.63
#Mann=5,-1,0
  4631.4    0.07       0  4820.5    0.16       0  4985.2    0.07       0
  4989.2    0.16       0  5257.2   0.035       0
Bank Sta=4985.2,4989.2
Exp/Cntr=0.3,0.1

Type RM Length L Ch R = 1,7442,135,135,135
BEGIN DESCRIPTION:
Elm 01 09 3755
END DESCRIPTION:
XS GIS Cut Line= 3
      1557982.05      6780308.37      1558204.33      6780305.78
      1558890.51      6780147.02
#Sta/Elev= 30
  4777.7 1944.71  4797.0 1943.61  4870.7 1938.50  4910.7 1936.66  4920.7 1937.77
  4950.7 1937.28  4990.7 1938.35  4997.8 1935.79  5002.9 1935.79  5007.1 1932.06
  5007.3 1931.56  5011.1 1932.06  5014.2 1932.58  5021.2 1937.66  5113.6 1938.15
  5185.0 1937.67  5195.7 1938.41  5298.3 1937.40  5323.4 1936.92  5366.1 1932.88
  5380.5 1933.71  5403.9 1933.35  5462.6 1933.70  5483.1 1936.81  5498.3 1937.43
  5504.5 1936.25  5524.2 1939.35  5679.6 1939.74  5698.6 1939.41  5704.3 1938.50
#Mann=7,-1,0
  4777.7    0.07       0  4797.0    0.16       0  5007.1    0.07       0
  5011.1    0.16       0  5403.9   0.035       0  5498.3    0.07       0
  5679.6   0.035       0
Bank Sta=5007.1,5011.1
Exp/Cntr=0.3,0.1

Type RM Length L Ch R = 1,7307,461,461,461
BEGIN DESCRIPTION:
Elm 01 09 7223.601
END DESCRIPTION:
XS GIS Cut Line= 3
      1557927.39      6780498.48      1558204.23      6780440.70
      1558829.99      6780213.00
#Sta/Elev= 30
  4717.2 1943.80  4765.8 1941.73  4787.7 1939.13  4842.2 1936.74  5003.1 1937.13
  5011.5 1934.50  5017.6 1931.54  5017.9 1931.04  5021.6 1931.54  5025.0 1932.11
  5032.7 1937.35  5309.9 1936.33  5345.4 1934.54  5370.7 1932.04  5406.6 1932.84
  5416.3 1933.75  5426.5 1934.42  5431.9 1933.44  5447.8 1933.64  5457.1 1934.52
  5469.0 1936.96  5487.7 1936.37  5493.0 1937.40  5511.6 1935.49  5518.3 1935.54
  5543.5 1935.91  5554.2 1937.46  5576.1 1938.47  5628.7 1939.61  5665.9 1938.73
#Mann=7,-1,0
  4717.2   0.035       0  4787.7    0.16       0  5017.6    0.07       0
  5021.6    0.16       0  5309.9    0.07       0  5416.3   0.035       0
  5576.1    0.07       0
Bank Sta=5017.6,5021.6
Exp/Cntr=0.3,0.1

Type RM Length L Ch R = 1,6846,383,383,383
BEGIN DESCRIPTION:
Elm 01 09 6846.3
END DESCRIPTION:
XS GIS Cut Line= 3
      1558041.96      6780883.91      1558409.17      6780641.71
      1558921.06      6780264.93
#Sta/Elev= 30
  4560.3 1934.53  4611.8 1935.65  4812.9 1935.73  4863.4 1931.10  4885.1 1933.23
  4891.1 1936.43  4906.2 1937.62  4948.3 1932.93  4999.0 1933.27  5007.4 1931.34
  5043.6 1935.12  5164.7 1935.44  5185.5 1934.03  5200.2 1931.15  5219.0 1931.04
  5219.3 1930.54  5223.0 1931.04  5224.2 1931.09  5255.5 1932.66  5285.8 1932.97
  5293.0 1934.80  5315.1 1935.95  5386.1 1935.41  5429.6 1936.03  5436.2 1937.58
  5496.7 1938.07  5562.8 1938.25  5592.8 1938.22  5615.9 1936.35  5635.8 1937.95
#Mann=8,-1,0
  4560.3    0.07       0  4611.8    0.16       0  5219.0    0.07       0
  5223.0    0.16       0  5224.2    0.07       0  5255.5   0.035       0
  5496.7    0.07       0  5562.8   0.035       0
Bank Sta=5219,5223
Exp/Cntr=0.3,0.1

Type RM Length L Ch R = 1,6463,190,190,190
BEGIN DESCRIPTION:
Elm 01 09 6463.42
END DESCRIPTION:
XS GIS Cut Line= 3
      1558044.60      6781050.56      1558724.28      6780696.39
      1559013.32      6780329.23
#Sta/Elev= 30
  4241.8 1934.24  4305.8 1934.06  4467.8 1934.17  4490.3 1933.65  4524.2 1930.03
  4546.7 1933.00  4667.2 1934.45  4777.7 1932.94  4816.3 1930.73  4848.0 1931.32
  4888.2 1931.82  4902.6 1928.67  4902.9 1928.17  4906.7 1928.67  4910.3 1931.66
  4941.4 1934.06  4976.6 1930.65  5010.4 1930.73  5071.1 1934.86  5105.4 1935.71
  5128.9 1934.21  5143.3 1936.01  5167.2 1936.08  5199.4 1936.51  5213.8 1935.00
  5243.4 1936.01  5292.4 1934.30  5391.8 1938.77  5420.7 1938.13  5475.5 1939.90
#Mann=8,-1,0
  4241.8    0.07       0  4305.8    0.16       0  4848.0    0.07       0
  4902.6    0.07       0  4906.7    0.07       0  5105.4   0.035       0
  5167.2    0.07       0  5243.4   0.035       0
Bank Sta=4902.6,4906.7
Exp/Cntr=0.3,0.1

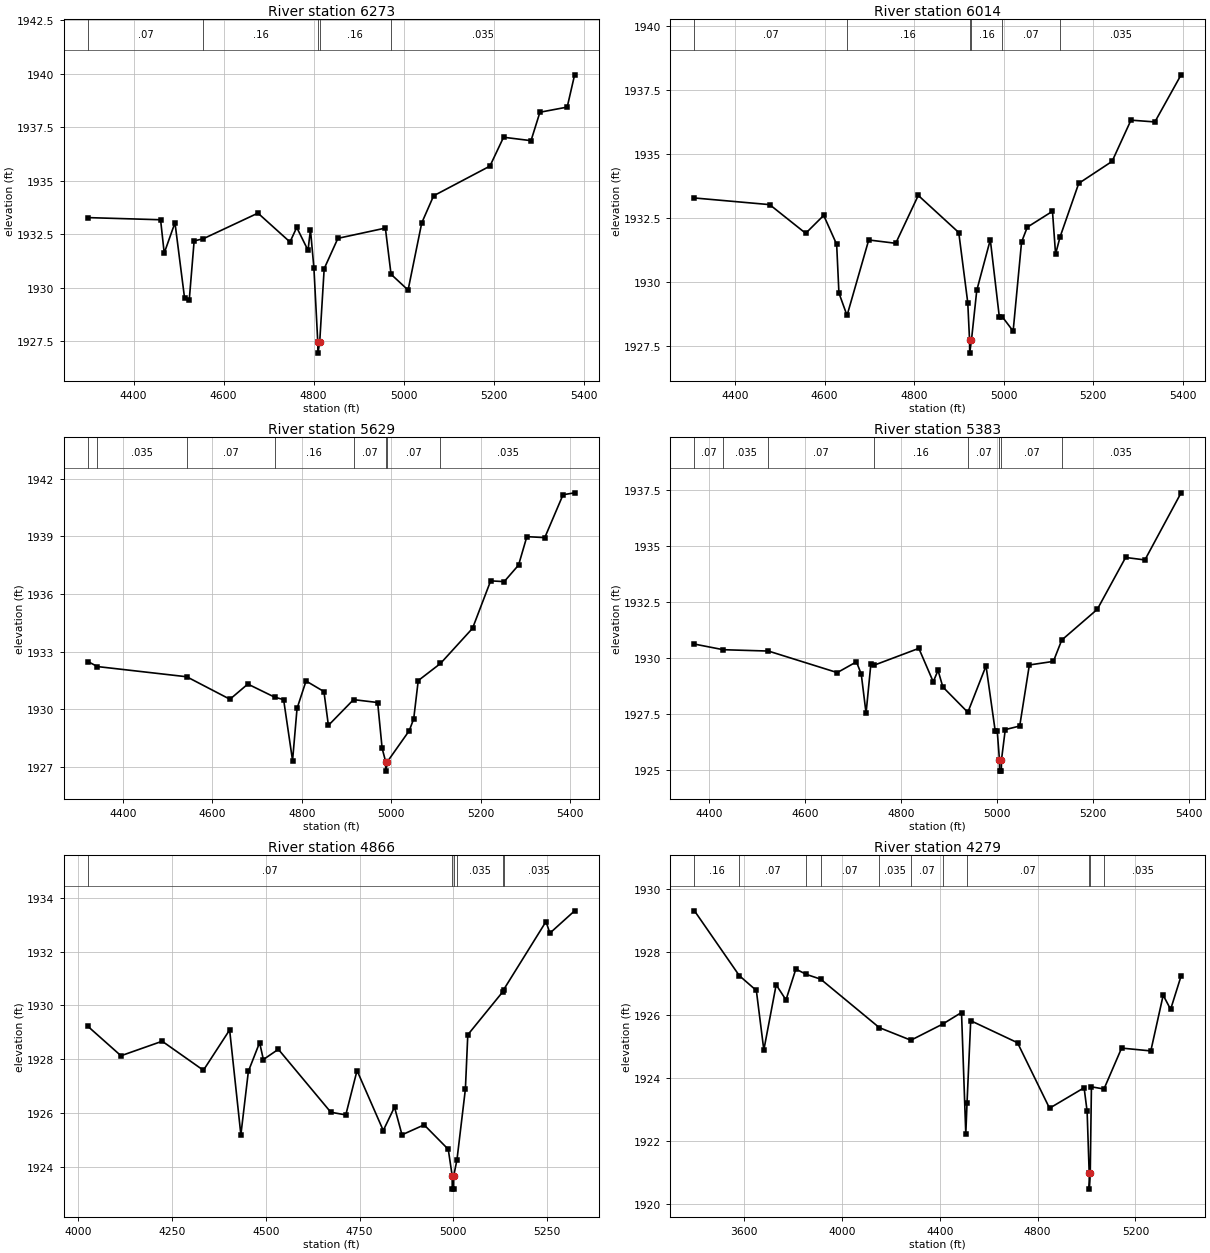
Type RM Length L Ch R = 1,6273,259,259,259
BEGIN DESCRIPTION:
Elm 01 09 6272.53
END DESCRIPTION:
XS GIS Cut Line= 3
      1558143.53      6781092.23      1558747.72      6780870.87
      1559181.30      6780808.56
#Sta/Elev= 30
  4298.7 1933.27  4460.0 1933.17  4468.1 1931.61  4492.0 1933.03  4513.3 1929.51
  4523.8 1929.43  4534.6 1932.18  4554.8 1932.28  4676.4 1933.48  4747.6 1932.13
  4762.6 1932.81  4787.7 1931.74  4793.1 1932.71  4800.8 1930.91  4809.4 1927.43
  4809.7 1926.93  4813.6 1927.43  4823.6 1930.88  4854.1 1932.30  4959.6 1932.78
  4972.2 1930.62  5010.1 1929.88  5040.4 1933.02  5066.8 1934.29  5192.0 1935.68
  5222.3 1937.03  5283.3 1936.87  5303.1 1938.20  5363.7 1938.44  5380.2 1939.95
#Mann=5,-1,0
  4298.7    0.07       0  4554.8    0.16       0  4809.4   0.035       0
  4813.6    0.16       0  4972.2   0.035       0
Bank Sta=4809.4,4813.6
Exp/Cntr=0.3,0.1

Type RM Length L Ch R = 1,6014,385,385,385
BEGIN DESCRIPTION:
Elm 01 09 6013.86
END DESCRIPTION:
XS GIS Cut Line= 3
      1558068.01      6781175.56      1558758.13      6781105.25
      1559131.36      6780983.43
#Sta/Elev= 30
  4309.7 1933.30  4477.6 1933.04  4558.0 1931.92  4598.2 1932.62  4627.1 1931.49
  4632.2 1929.59  4650.3 1928.71  4698.7 1931.66  4759.0 1931.53  4809.3 1933.40
  4899.7 1931.95  4919.8 1929.21  4923.8 1927.74  4924.1 1927.24  4928.0 1927.74
  4939.9 1929.69  4970.1 1931.67  4990.2 1928.66  4996.4 1928.67  5021.1 1928.10
  5039.9 1931.58  5052.7 1932.16  5108.9 1932.78  5115.8 1931.11  5125.9 1931.78
  5167.5 1933.87  5242.0 1934.73  5284.1 1936.34  5337.5 1936.27  5396.0 1938.11
#Mann=6,-1,0
  4309.7    0.07       0  4650.3    0.16       0  4923.8    0.07       0
  4928.0    0.16       0  4996.4    0.07       0  5125.9   0.035       0
Bank Sta=4923.8,4928
Exp/Cntr=0.3,0.1

Type RM Length L Ch R = 1,5629,246,246,246
BEGIN DESCRIPTION:
Elm 01 09 5629.48
END DESCRIPTION:
XS GIS Cut Line= 3
      1558127.94      6781352.64      1558799.80      6781376.08
      1559210.62      6781313.68
#Sta/Elev= 30
  4322.3 1932.49  4343.4 1932.23  4543.0 1931.70  4639.6 1930.53  4679.6 1931.32
  4739.4 1930.64  4759.6 1930.51  4779.6 1927.34  4789.6 1930.05  4809.7 1931.48
  4849.7 1930.93  4859.7 1929.17  4915.9 1930.51  4969.8 1930.36  4979.8 1927.98
  4987.6 1927.29  4987.8 1926.79  4991.8 1927.29  5040.3 1928.89  5050.4 1929.51
  5060.5 1931.50  5110.2 1932.39  5181.9 1934.22  5222.4 1936.69  5252.7 1936.65
  5284.8 1937.51  5303.3 1938.99  5343.4 1938.94  5384.2 1941.17  5410.1 1941.27
#Mann=8,-1,0
  4322.3    0.07       0  4343.4   0.035       0  4543.0    0.07       0
  4739.4    0.16       0  4915.9    0.07       0  4987.6    0.07       0
  4991.8    0.07       0  5110.2   0.035       0
Bank Sta=4987.6,4991.8
Exp/Cntr=0.3,0.1

Type RM Length L Ch R = 1,5383,517,517,517
BEGIN DESCRIPTION:
Elm 01 09 5383.395
END DESCRIPTION:
XS GIS Cut Line= 3
      1558177.38      6781594.83      1558808.36      6781589.76
      1559190.17      6781558.39
#Sta/Elev= 30
  4369.0 1930.62  4429.0 1930.37  4523.1 1930.31  4666.6 1929.35  4706.6 1929.83
  4716.6 1929.28  4726.6 1927.54  4736.6 1929.73  4742.2 1929.67  4836.6 1930.43
  4866.6 1928.94  4876.6 1929.45  4886.6 1928.71  4938.7 1927.58  4976.6 1929.65
  4995.8 1926.74  5000.0 1926.74  5004.6 1925.46  5004.8 1924.96  5008.5 1924.96
  5008.8 1925.46  5016.7 1926.81  5046.8 1926.97  5066.9 1929.69  5117.0 1929.85
  5134.4 1930.80  5208.5 1932.17  5267.5 1934.48  5307.7 1934.37  5383.1 1937.36
#Mann=8,-1,0
  4369.0    0.07       0  4429.0   0.035       0  4523.1    0.07       0
  4742.2    0.16       0  4938.7    0.07       0  5004.6    0.07       0
  5008.8    0.07       0  5134.4   0.035       0
Bank Sta=5004.6,5008.8
Exp/Cntr=0.3,0.1

Type RM Length L Ch R = 1,4866,587,587,587
BEGIN DESCRIPTION:
Elm 01 09 3762
END DESCRIPTION:
XS GIS Cut Line= 3
      1558166.99      6781896.92      1559044.59      6781899.52
      1559448.28      6781779.71
#Sta/Elev= 30
  4025.4 1929.22  4113.4 1928.13  4223.4 1928.67  4333.4 1927.59  4403.4 1929.09
  4433.4 1925.19  4453.4 1927.55  4483.4 1928.62  4493.4 1927.99  4533.4 1928.37
  4673.4 1926.03  4713.4 1925.93  4743.4 1927.58  4813.4 1925.35  4843.4 1926.22
  4863.4 1925.19  4922.5 1925.56  4986.9 1924.65  4997.3 1923.67  4997.5 1923.17
  5001.2 1923.17  5001.5 1923.67  5010.1 1924.26  5032.6 1926.89  5039.0 1928.91
  5132.4 1930.51  5134.8 1930.59  5247.7 1933.12  5258.1 1932.69  5324.1 1933.52
#Mann=6,-1,0
  4025.4    0.07       0  4997.3    0.07       0  5001.5    0.07       0
  5010.1   0.035       0  5132.4    0.07       0  5134.8   0.035       0
Bank Sta=4997.3,5001.5
Exp/Cntr=0.3,0.1

Type RM Length L Ch R = 1,4279,332,332,332
BEGIN DESCRIPTION:
Elm 01 09 3764
END DESCRIPTION:
XS GIS Cut Line= 3
      1557513.37      6782212.02      1559105.15      6782404.74
      1559487.28      6782344.84
#Sta/Elev= 30
  3396.6 1929.32  3580.1 1927.26  3649.7 1926.79  3680.3 1924.90  3730.7 1926.97
  3770.9 1926.49  3811.2 1927.47  3854.4 1927.30  3912.7 1927.15  4152.6 1925.61
  4281.8 1925.21  4411.1 1925.72  4488.8 1926.09  4506.3 1922.23  4511.4 1923.23
  4526.4 1925.83  4717.8 1925.13  4848.8 1923.05  4990.2 1923.70  5002.5 1922.95
  5011.0 1920.98  5011.3 1920.48  5015.3 1920.98  5020.1 1923.73  5071.4 1923.66
  5143.5 1924.96  5263.0 1924.87  5313.6 1926.64  5344.0 1926.19  5386.8 1927.25
#Mann=11,-1,0
  3396.6    0.16       0  3580.1    0.07       0  3854.4   0.035       0
  3912.7    0.07       0  4152.6   0.035       0  4281.8    0.07       0
  4411.1   0.035       0  4511.4    0.07       0  5011.0    0.07       0
  5015.3    0.07       0  5071.4   0.035       0
Bank Sta=5011,5015.3
Exp/Cntr=0.3,0.1

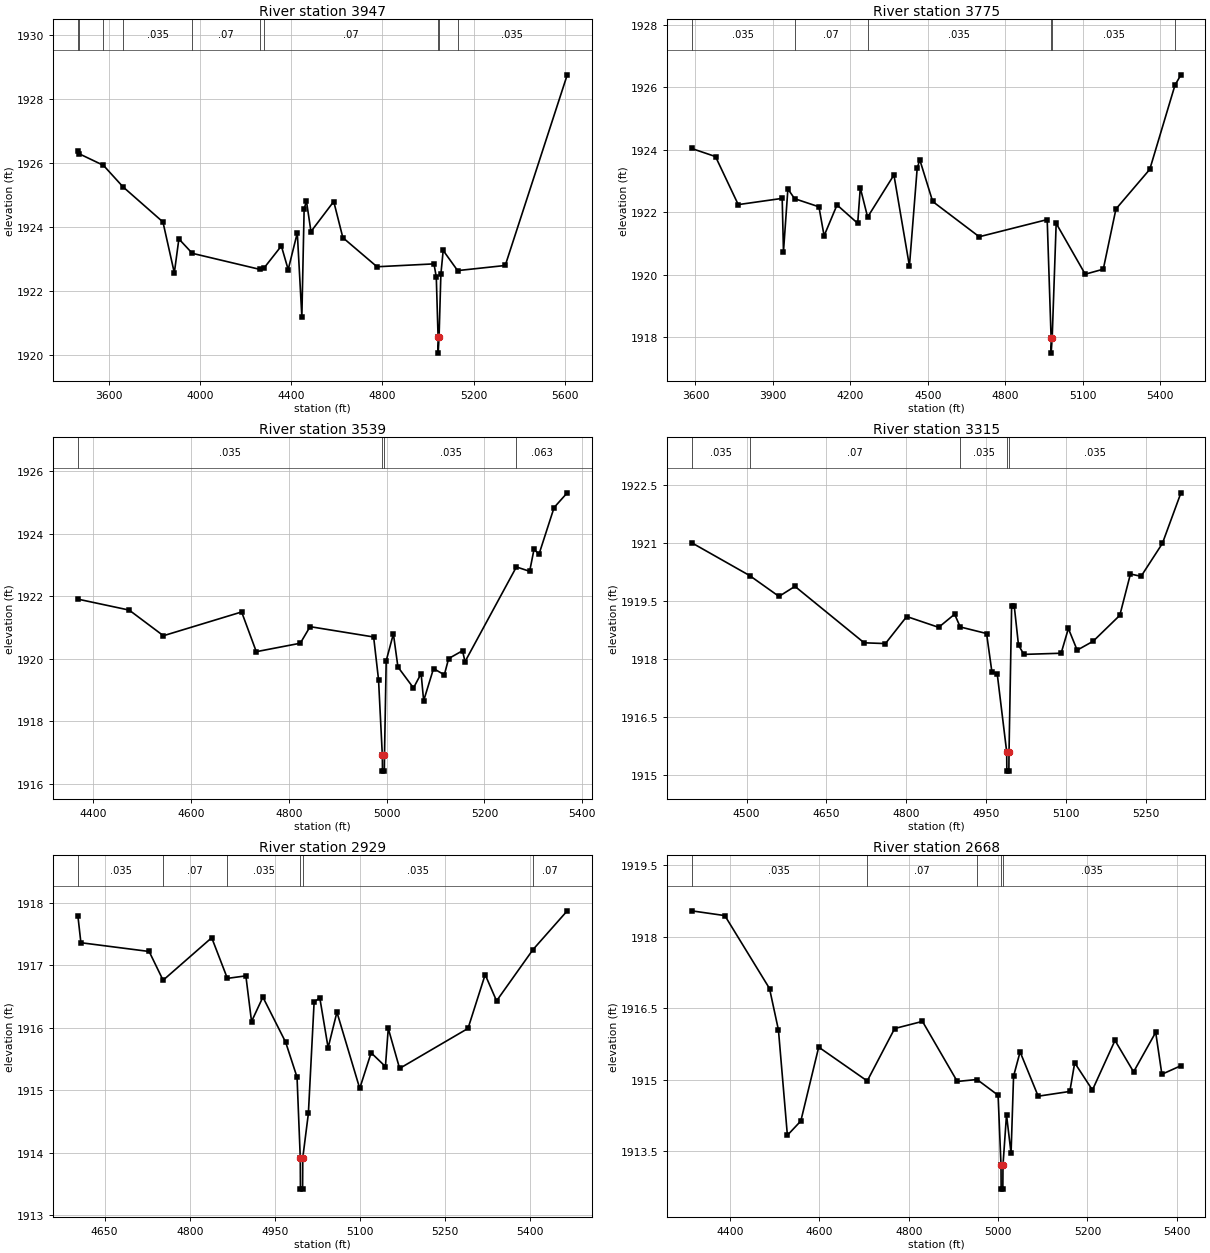
Type RM Length L Ch R = 1,3947,172,172,172
BEGIN DESCRIPTION:
Elm 01 09 3766
END DESCRIPTION:
XS GIS Cut Line= 3
      1557531.54      6782722.44      1559068.84      6782724.84
      1559674.76      6782641.71
#Sta/Elev= 30
  3462.7 1926.38  3468.9 1926.28  3575.0 1925.92  3660.5 1925.25  3836.2 1924.15
  3886.2 1922.56  3906.2 1923.62  3965.1 1923.17  4260.6 1922.67  4278.9 1922.70
  4356.2 1923.40  4386.2 1922.66  4426.2 1923.81  4446.2 1921.19  4456.2 1924.55
  4466.2 1924.81  4486.2 1923.85  4586.2 1924.79  4626.2 1923.66  4776.2 1922.75
  5026.4 1922.84  5036.5 1922.43  5044.4 1920.55  5044.7 1920.05  5048.7 1920.55
  5056.7 1922.52  5066.8 1923.26  5130.2 1922.63  5339.3 1922.79  5611.6 1928.75
#Mann=10,-1,0
  3462.7    0.07       0  3468.9   0.035       0  3575.0    0.07       0
  3660.5   0.035       0  3965.1    0.07       0  4260.6   0.035       0
  4278.9    0.07       0  5044.4    0.07       0  5048.7    0.07       0
  5130.2   0.035       0
Bank Sta=5044.4,5048.7
Exp/Cntr=0.3,0.1

Type RM Length L Ch R = 1,3775,236,236,236
BEGIN DESCRIPTION:
Elm 01 09 3768
END DESCRIPTION:
XS GIS Cut Line= 3
      1557742.50      6782943.79      1559155.16      6782860.68
      1559635.70      6782844.83
#Sta/Elev= 30
  3584.9 1924.04  3677.6 1923.78  3765.7 1922.24  3935.9 1922.44  3940.9 1920.73
  3958.0 1922.74  3984.1 1922.43  4078.3 1922.17  4098.3 1921.24  4148.4 1922.23
  4228.5 1921.64  4238.5 1922.78  4266.9 1921.84  4368.8 1923.19  4428.9 1920.27
  4458.9 1923.40  4468.9 1923.68  4519.0 1922.34  4699.3 1921.21  4962.6 1921.76
  4977.7 1917.98  4977.9 1917.48  4982.0 1917.98  4997.4 1921.64  5109.9 1920.01
  5179.9 1920.17  5229.0 1922.10  5360.0 1923.37  5457.7 1926.07  5480.8 1926.40
#Mann=6,-1,0
  3584.9   0.035       0  3984.1    0.07       0  4266.9   0.035       0
  4977.7   0.035       0  4982.0   0.035       0  5457.7   0.063       0
Bank Sta=4977.7,4982
Exp/Cntr=0.3,0.1

Type RM Length L Ch R = 1,3539,224,224,224
BEGIN DESCRIPTION:
Elm 01 09 3774
END DESCRIPTION:
XS GIS Cut Line= 3
      1558620.14      6783045.35      1559251.51      6783039.27
      1559611.15      6782954.48
#Sta/Elev= 30
  4368.6 1921.91  4473.5 1921.56  4543.5 1920.74  4703.5 1921.50  4733.5 1920.23
  4823.5 1920.50  4843.5 1921.03  4973.5 1920.70  4983.5 1919.34  4991.3 1916.91
  4991.6 1916.41  4995.4 1916.41  4995.7 1916.91  4999.2 1919.94  5013.9 1920.80
  5023.2 1919.74  5055.0 1919.07  5070.6 1919.53  5075.8 1918.66  5096.0 1919.69
  5118.1 1919.49  5126.9 1920.01  5155.3 1920.26  5160.4 1919.91  5265.5 1922.94
  5292.6 1922.80  5301.5 1923.50  5311.8 1923.35  5342.6 1924.84  5369.5 1925.31
#Mann=4,-1,0
  4368.6   0.035       0  4991.3   0.035       0  4995.7   0.035       0
  5265.5   0.063       0
Bank Sta=4991.3,4995.7
Exp/Cntr=0.3,0.1

Type RM Length L Ch R = 1,3315,386,386,386
BEGIN DESCRIPTION:
Elm 01 09 3772
END DESCRIPTION:
XS GIS Cut Line= 3
      1558700.85      6783238.06      1559304.07      6783247.85
      1559619.82      6783232.99
#Sta/Elev= 30
  4396.7 1921.00  4505.7 1920.15  4560.9 1919.61  4590.9 1919.87  4720.9 1918.41
  4760.9 1918.39  4800.9 1919.09  4860.9 1918.81  4890.9 1919.15  4901.4 1918.82
  4950.9 1918.65  4960.9 1917.66  4970.9 1917.61  4988.7 1915.59  4989.0 1915.09
  4992.8 1915.09  4993.1 1915.59  4998.0 1919.35  5003.0 1919.35  5010.9 1918.35
  5021.0 1918.11  5091.0 1918.14  5104.6 1918.78  5121.1 1918.22  5151.1 1918.45
  5201.2 1919.12  5221.2 1920.19  5241.2 1920.13  5281.2 1920.98  5316.1 1922.29
#Mann=5,-1,0
  4396.7   0.035       0  4505.7    0.07       0  4901.4   0.035       0
  4988.7   0.035       0  4993.1   0.035       0
Bank Sta=4988.7,4993.1
Exp/Cntr=0.3,0.1

Type RM Length L Ch R = 1,2929,261,261,261
BEGIN DESCRIPTION:
Elm 01 09 3746
END DESCRIPTION:
XS GIS Cut Line= 3
      1558859.67      6783589.62      1559255.80      6783617.30
      1559719.03      6783571.40
#Sta/Elev= 30
  4602.9 1917.79  4608.2 1917.36  4728.5 1917.22  4753.1 1916.76  4838.8 1917.44
  4866.4 1916.79  4899.0 1916.83  4909.0 1916.10  4929.0 1916.49  4969.1 1915.77
  4989.2 1915.21  4994.9 1913.92  4995.2 1913.42  4999.0 1913.42  4999.3 1913.92
  5009.2 1914.63  5019.3 1916.41  5029.3 1916.48  5044.0 1915.68  5059.5 1916.25
  5099.7 1915.03  5119.8 1915.60  5145.0 1915.38  5150.0 1915.99  5170.0 1915.35
  5290.6 1915.99  5320.8 1916.85  5340.9 1916.43  5405.1 1917.25  5465.5 1917.87
#Mann=6,-1,0
  4602.9   0.035       0  4753.1    0.07       0  4866.4   0.035       0
  4994.9   0.035       0  4999.3   0.035       0  5405.1    0.07       0
Bank Sta=4994.9,4999.3
Exp/Cntr=0.3,0.1

Type RM Length L Ch R = 1,2668,339,339,339
BEGIN DESCRIPTION:
Elm 01 09 3770
END DESCRIPTION:
XS GIS Cut Line= 3
      1558570.63      6783896.92      1559256.38      6783878.34
      1559660.85      6783816.33
#Sta/Elev= 30
  4314.0 1918.54  4388.4 1918.44  4488.4 1916.91  4508.4 1916.04  4528.4 1913.83
  4558.5 1914.13  4598.5 1915.68  4707.1 1914.97  4768.5 1916.07  4830.7 1916.22
  4908.6 1914.96  4952.9 1915.00  5000.0 1914.67  5006.5 1913.20  5006.8 1912.70
  5010.6 1912.70  5010.9 1913.20  5018.8 1914.26  5029.0 1913.45  5034.6 1915.07
  5049.2 1915.58  5089.7 1914.65  5160.5 1914.75  5171.4 1915.35  5211.1 1914.78
  5261.6 1915.82  5303.2 1915.16  5352.7 1915.99  5366.5 1915.11  5409.2 1915.29
#Mann=5,-1,0
  4314.0   0.035       0  4707.1    0.07       0  4952.9   0.035       0
  5006.5   0.035       0  5010.9   0.035       0
Bank Sta=5006.5,5010.9
Exp/Cntr=0.3,0.1

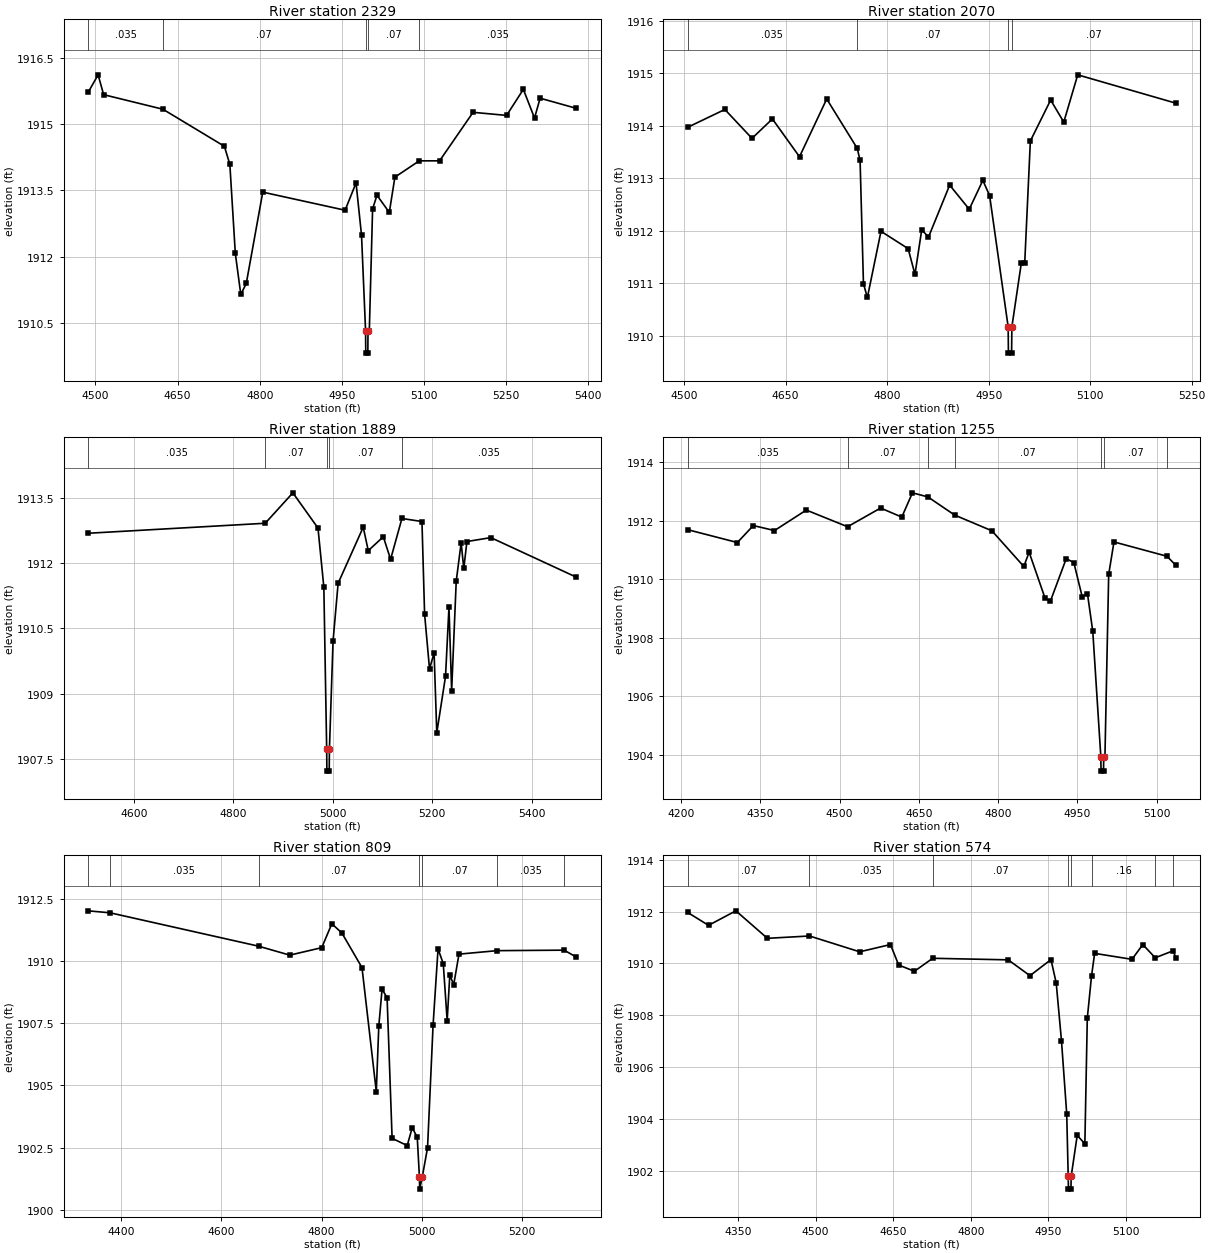
Type RM Length L Ch R = 1,2329,259,259,259
BEGIN DESCRIPTION:
Elm 01 09 3743
END DESCRIPTION:
XS GIS Cut Line= 3
      1558846.69      6784217.23      1559359.16      6784186.28
      1559729.99      6784113.00
#Sta/Elev= 30
  4486.6 1915.72  4504.9 1916.12  4515.0 1915.67  4623.2 1915.34  4735.4 1914.50
  4745.4 1914.09  4755.4 1912.07  4765.4 1911.14  4775.4 1911.39  4805.5 1913.46
  4955.8 1913.05  4975.8 1913.67  4985.8 1912.48  4993.2 1910.31  4993.5 1909.81
  4997.3 1909.81  4997.6 1910.31  5000.0 1910.31  5006.0 1913.08  5014.0 1913.39
  5036.5 1913.00  5046.7 1913.80  5091.2 1914.17  5128.3 1914.17  5189.4 1915.27
  5250.6 1915.20  5281.2 1915.79  5301.6 1915.14  5311.8 1915.59  5378.0 1915.36
#Mann=5,-1,0
  4486.6   0.035       0  4623.2    0.07       0  4993.2    0.07       0
  4997.6    0.07       0  5091.2   0.035       0
Bank Sta=4993.2,4997.6
Exp/Cntr=0.3,0.1

Type RM Length L Ch R = 1,2070,181,181,181
BEGIN DESCRIPTION:
Elm 01 09 3732
END DESCRIPTION:
XS GIS Cut Line= 3
      1559010.11      6784433.81      1559503.41      6784394.05
      1559729.98      6784390.41
#Sta/Elev= 30
  4505.1 1913.97  4560.2 1914.31  4600.3 1913.76  4630.4 1914.13  4670.5 1913.41
  4710.7 1914.51  4755.8 1913.57  4760.0 1913.34  4765.0 1910.99  4770.8 1910.73
  4790.9 1911.99  4831.0 1911.66  4841.1 1911.17  4851.1 1912.02  4861.1 1911.88
  4892.4 1912.87  4921.3 1912.41  4941.4 1912.96  4951.4 1912.67  4978.8 1910.17
  4979.2 1909.67  4983.9 1909.67  4984.3 1910.17  4998.3 1911.39  5003.3 1911.39
  5011.6 1913.71  5041.6 1914.49  5061.0 1914.07  5081.6 1914.97  5226.6 1914.43
#Mann=4,-1,0
  4505.1   0.035       0  4755.8    0.07       0  4978.8    0.07       0
  4984.3    0.07       0
Bank Sta=4978.8,4984.3
Exp/Cntr=0.3,0.1

Type RM Length L Ch R = 1,1889,634,634,634
BEGIN DESCRIPTION:
Elm 01 09 3730
END DESCRIPTION:
XS GIS Cut Line= 3
      1558927.63      6784611.76      1559574.32      6784516.27
      1559880.04      6784635.65
#Sta/Elev= 30
  4508.2 1912.69  4864.4 1912.92  4920.0 1913.62  4970.5 1912.81  4982.3 1911.45
  4988.0 1907.72  4988.4 1907.22  4993.1 1907.22  4993.5 1907.72  5000.8 1910.21
  5011.0 1911.54  5061.5 1912.83  5071.6 1912.29  5101.9 1912.61  5116.5 1912.09
  5139.3 1913.03  5179.6 1912.96  5184.9 1910.83  5194.8 1909.57  5204.0 1909.94
  5209.4 1908.10  5227.0 1909.40  5233.9 1910.99  5239.3 1909.07  5248.5 1911.59
  5258.4 1912.47  5263.7 1911.88  5270.0 1912.50  5318.1 1912.59  5490.1 1911.68
#Mann=5,-1,0
  4508.2   0.035       0  4864.4    0.07       0  4988.0    0.07       0
  4993.5    0.07       0  5139.3   0.035       0
Bank Sta=4988,4993.5
Exp/Cntr=0.3,0.1

Type RM Length L Ch R = 1,1255,446,446,446
BEGIN DESCRIPTION:
Elm 01 09 3728
END DESCRIPTION:
XS GIS Cut Line= 3
      1559021.11      6784719.83      1559805.86      6784787.96
      1559941.51      6784774.67
#Sta/Elev= 30
  4212.3 1911.70  4306.5 1911.26  4336.7 1911.84  4376.8 1911.67  4437.0 1912.37
  4515.1 1911.80  4577.6 1912.44  4617.7 1912.13  4637.8 1912.96  4667.1 1912.82
  4717.6 1912.20  4788.3 1911.66  4848.6 1910.44  4858.6 1910.93  4888.7 1909.36
  4898.8 1909.25  4928.9 1910.71  4943.3 1910.57  4959.0 1909.41  4969.0 1909.51
  4979.1 1908.22  4994.3 1903.94  4994.7 1903.44  4999.4 1903.44  4999.8 1903.94
  5002.1 1903.94  5009.2 1910.17  5019.2 1911.28  5119.5 1910.79  5136.3 1910.48
#Mann=7,-1,0
  4212.3   0.035       0  4515.1    0.07       0  4667.1   0.035       0
  4717.6    0.07       0  4994.3    0.07       0  4999.8    0.07       0
  5119.5   0.035       0
Bank Sta=4994.3,4999.8
Exp/Cntr=0.3,0.1

Type RM Length L Ch R = 1,809,235,235,235
BEGIN DESCRIPTION:
Elm 01 09 3723
END DESCRIPTION:
XS GIS Cut Line= 3
      1559010.25      6785196.12      1559674.25      6785157.99
      1559969.29      6785070.63
#Sta/Elev= 30
  4334.9 1912.01  4378.9 1911.93  4674.5 1910.59  4736.7 1910.23  4800.4 1910.53
  4820.5 1911.49  4840.5 1911.12  4880.6 1909.73  4909.1 1904.75  4914.1 1907.39
  4920.6 1908.86  4930.6 1908.52  4940.6 1902.87  4970.7 1902.58  4980.7 1903.30
  4990.7 1902.91  4995.0 1901.33  4995.5 1900.83  5000.8 1901.33  5011.2 1902.49
  5022.2 1907.41  5032.1 1910.48  5042.5 1909.89  5050.3 1907.60  5055.5 1909.42
  5063.4 1909.05  5073.8 1910.27  5149.8 1910.41  5283.3 1910.43  5307.7 1910.15
#Mann=7,-1,0
  4334.9    0.07       0  4378.9   0.035       0  4674.5    0.07       0
  4995.0    0.07       0  5000.8    0.07       0  5149.8   0.035       0
  5283.3    0.07       0
Bank Sta=4995,5000.8
Exp/Cntr=0.3,0.1

Type RM Length L Ch R = 1,574,407,407,407
BEGIN DESCRIPTION:
Elm 01 09 3719
END DESCRIPTION:
XS GIS Cut Line= 3
      1559073.03      6785460.51      1559829.53      6785328.08
      1559973.80      6785227.46
#Sta/Elev= 30
  4252.6 1911.97  4293.1 1911.47  4346.0 1912.03  4406.9 1910.97  4488.3 1911.06
  4585.3 1910.45  4644.8 1910.73  4660.7 1909.94  4691.1 1909.70  4726.5 1910.20
  4872.4 1910.14  4914.5 1909.53  4955.1 1910.15  4965.2 1909.25  4975.4 1907.02
  4985.5 1904.21  4988.4 1901.80  4988.9 1901.30  4993.7 1901.30  4994.2 1901.80
  5005.8 1903.37  5020.6 1903.05  5025.3 1907.89  5033.5 1909.52  5039.5 1910.39
  5111.7 1910.16  5132.6 1910.73  5156.6 1910.22  5191.3 1910.49  5196.5 1910.21
#Mann=8,-1,0
  4252.6    0.07       0  4488.3   0.035       0  4726.5    0.07       0
  4988.4    0.07       0  4994.2    0.07       0  5033.5    0.16       0
  5156.6   0.035       0  5191.3    0.07       0
Bank Sta=4988.4,4994.2
Exp/Cntr=0.3,0.1

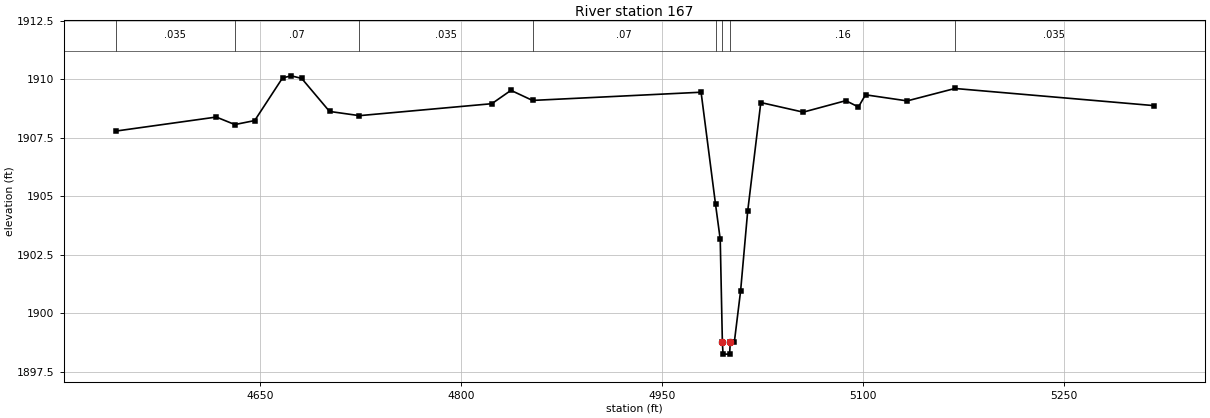
Type RM Length L Ch R = 1,167,0,0,0
BEGIN DESCRIPTION:
Elm 01 09 3717
END DESCRIPTION:
XS GIS Cut Line= 3
      1559583.88      6785962.43      1559936.92      6785670.35
      1560040.97      6785370.91
#Sta/Elev= 30
  4541.8 1907.78  4617.0 1908.38  4630.9 1908.06  4645.7 1908.23  4666.5 1910.05
  4673.0 1910.14  4680.8 1910.03  4701.6 1908.62  4723.9 1908.44  4822.8 1908.95
  4837.1 1909.52  4853.2 1909.09  4979.1 1909.44  4989.9 1904.65  4993.4 1903.16
  4995.0 1898.76  4995.5 1898.26  5000.4 1898.26  5000.9 1898.76  5003.9 1898.76
  5008.6 1900.95  5013.9 1904.36  5023.7 1909.00  5055.4 1908.59  5087.2 1909.08
  5096.6 1908.81  5101.9 1909.33  5133.0 1909.07  5168.7 1909.60  5317.0 1908.87
#Mann=8,-1,0
  4541.8   0.035       0  4630.9    0.07       0  4723.9   0.035       0
  4853.2    0.07       0  4989.9    0.16       0  4995.0    0.07       0
  5000.9    0.16       0  5168.7   0.035       0
Bank Sta=4995,5000.9
Exp/Cntr=0.3,0.1

Chan Stop Cuts=-1