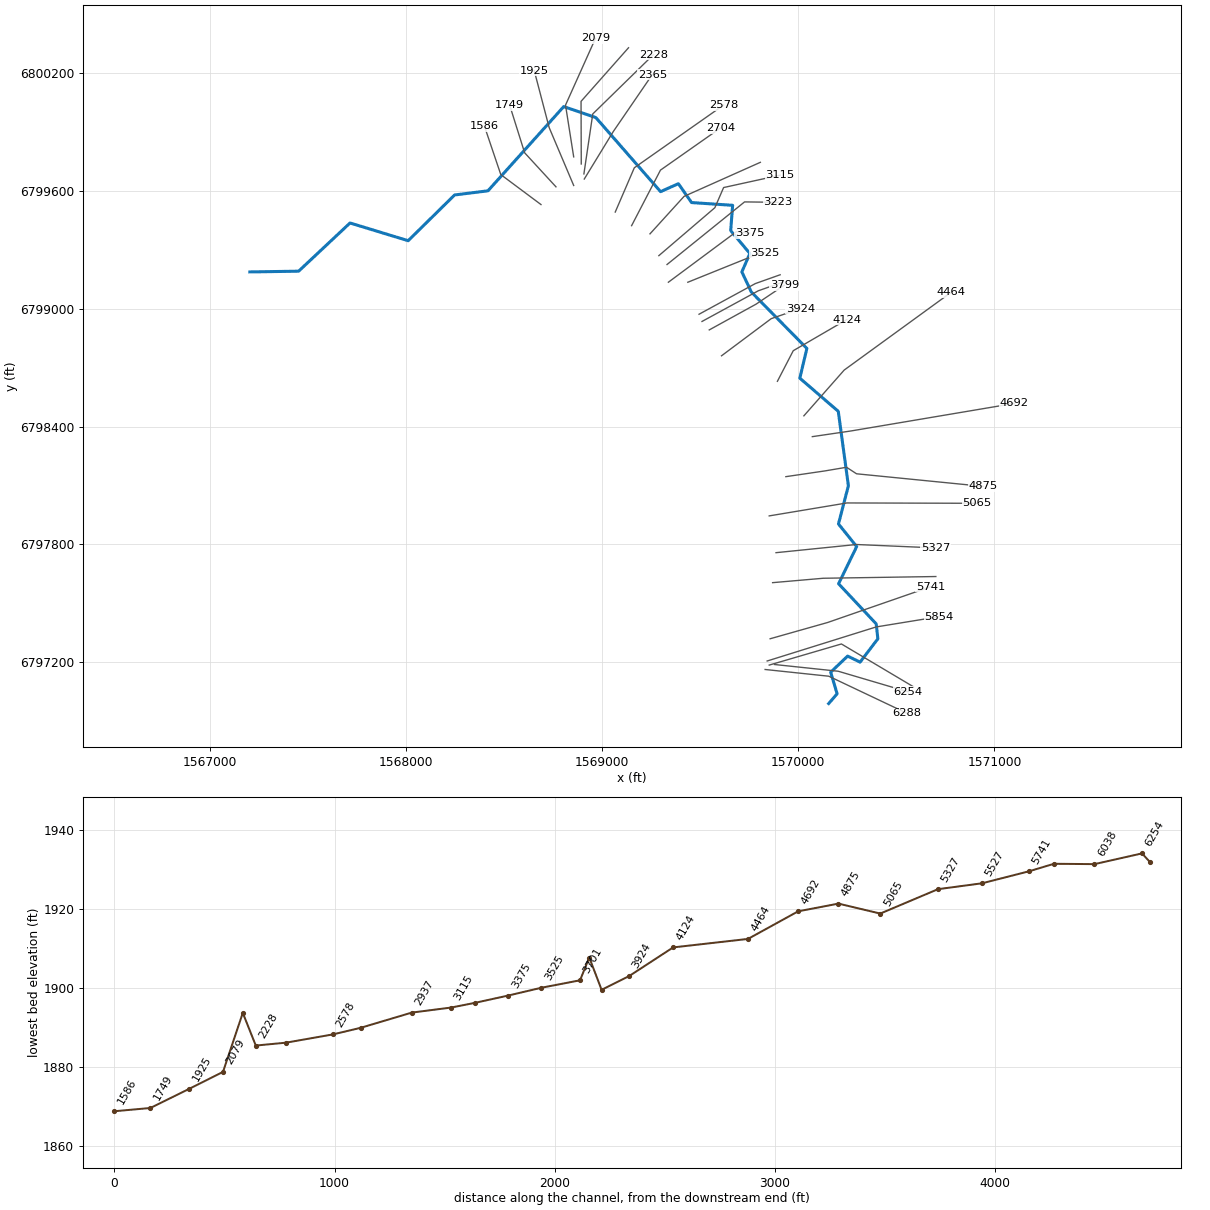
--- Elm 01 11.prj (project) ---

Proj Title=Elm 01 11 Base Level Engineering
Current Plan=p01
Default Exp/Contr=0.3,0.1
English Units
Geom File=g01
Flow File=f01
Plan File=p01
Y Axis Title=Elevation
X Axis Title(PF)=Main Channel Distance
X Axis Title(XS)=Station
BEGIN DESCRIPTION:
Elm 01 11
END DESCRIPTION:
DSS Export Rating Curves= 0
DSS Export Rating Curve Sorted= 0
DSS Export Volume Flow Curves= 0
DXF OffsetX= 0
DXF OffsetY= 0
DXF ScaleX= 1
DXF ScaleY= 10

--- Elm 01 11.p01 (plan) ---

Plan Title=Multiple Run
Program Version=4.10
Short Identifier=Multiple
Geom File=g01
Flow File=f01
Subcritical Flow
K Sum by GR= 0
Std Step Tol= 0.01
Critical Tol= 0.01
Num of Std Step Trials= 20
Max Error Tol= 0.3
Flow Tol Ratio= 0.001
Split Flow NTrial= 30
Split Flow Tol= 0.02
Split Flow Ratio= 0.02
Log Output Level= 0
Friction Slope Method= 1
Unsteady Friction Slope Method= 2
Unsteady Bridges Friction Slope Method= 1
Parabolic Critical Depth
Global Vel Dist= 1 , 1 , 1
Global Log Level= 0
CheckData=True
Encroach Param=-1 ,0,0, 0
BEGIN DESCRIPTION:
Multiple Run
END DESCRIPTION:
Computation Interval=1HOUR
Output Interval=1HOUR
Run HTab= 0
Run UNet= 0
Run PostProcess= 0
Run WQNet= 0
UNET Theta= 1
UNET Theta Warmup= 1
UNET ZTol= 0.02
UNET ZSATol= 0.05
UNET MxIter= 20
UNET MaxInSteps= 0
UNET DtIC= 0
UNET DtMin= 0
UNET MaxCRTS= 20
UNET WFStab= 2
UNET SFStab= 1
UNET WFX= 1
UNET SFX= 1
UNET DSS MLevel= 4
UNET DZMax Abort= 100
UNET Convert EG Bridges= 0
UNET Use Existing IB Tables=-1
UNET Froude Reduction=False
UNET Froude Limit= 1
UNET Froude Power= 10
UNET Time Slicing=0,0, 5
UNET Junction Losses=0
Instantaneous Interval=1HOUR
Write IC File= 0
Write IC File at Sim End=0
Echo Input=False
Echo Parameters=False
Echo Output=False
Write Detailed= 0
WQ AD Non Conservative
WQ ULTIMATE=-1
WQ Max Comp Step=1HOUR
WQ Output Interval=15MIN
WQ Output Selected Increments= 0
WQ Output face flow=0
WQ Output face velocity=0
WQ Output face area=0
WQ Output face dispersion=0
WQ Output cell volume=0
WQ Output cell surface area=0
WQ Output cell continuity=0
WQ Output cumulative cell continuity=0
WQ Output face conc=0
WQ Output face dconc_dx=0
WQ Output face courant=0
WQ Output face peclet=0
WQ Output face adv mass=0
WQ Output face disp mass=0
WQ Output cell mass=0
WQ Output cell source sink temp=0
WQ Output cell source sink nsm=0
WQ Output MaxMinRange=-1
WQ Daily Max Min Mean=-1
WQ Daily Range=0
WQ Daily Time=0
WQ Create Restart=0
WQ Fixed Restart=0
WQ System Summary=0
WQ Use Fixed Temperature=0
Sorting and Armoring Iterations= 10
XS Update Threshold= 0.02
Hydraulics Update Threshold= 0.02
Energy Slope Method= 1
Volume Change Method= 0
XS Weighting Method= 0
Number of US Weighted Cross Sections= 1
Number of DS Weighted Cross Sections= 1
Upstream XS Weight=0.25
Main XS Weight=0.5
Downstream XS Weight=0.25
Number of DS XS's Weighted with US Boundary= 1
Upstream Boundary Weight= 1
Weight of XSs Associated with US Boundary= 0
Number of US XS's Weighted with DS Boundary= 1
Downstream Boundary Weight= 0.5
Weight of XSs Associated with DS Boundary= 0.5
Sediment Output Level= 4
Mass or Volume Output= 0
Output Increment Type= 1
Profile and TS Output Increment= 10
XS Output Flag= 0
XS Output Increment= 10
Disregard all LS=0
Disregard all Conn=0
Disregard all Breaches=0
Disregard all Pumps=0

--- Elm 01 11.f01 (steady flow) ---

Flow Title=Multiple
Number of Profiles=7
Profile Names=10-year,25-year,50-year,1pct_min,100-year,1pct_plu,500-year
River Rch & RM= Elm 01 11,Reach-1,6288
     218     303     373     285     457     629     695
Boundary for River Rch & Prof#=Elm 01 11,Reach-1,1
Up Type=0
Dn Type=3
Dn Slope=0.005
Boundary for River Rch & Prof#=Elm 01 11,Reach-1,2
Up Type=0
Dn Type=3
Dn Slope=0.005
Boundary for River Rch & Prof#=Elm 01 11,Reach-1,3
Up Type=0
Dn Type=3
Dn Slope=0.005
Boundary for River Rch & Prof#=Elm 01 11,Reach-1,4
Up Type=0
Dn Type=3
Dn Slope=0.005
Boundary for River Rch & Prof#=Elm 01 11,Reach-1,5
Up Type=0
Dn Type=3
Dn Slope=0.005
Boundary for River Rch & Prof#=Elm 01 11,Reach-1,6
Up Type=0
Dn Type=3
Dn Slope=0.005
Boundary for River Rch & Prof#=Elm 01 11,Reach-1,7
Up Type=0
Dn Type=3
Dn Slope=0.005

--- Elm 01 11.g01 (geometry) ---

Geom Title=Existing Conditions
Program Version=4.10

River Reach=Elm 01 11       ,Reach-1
Reach XY= 30
        1570155.        6796988.      1570198.05      6797037.88
       1570165.2      6797147.73      1570251.65        6797230.
      1570315.02      6797199.23      1570405.68      6797317.92
      1570397.24      6797394.17      1570205.59      6797598.62
       1570297.7      6797788.08      1570204.96      6797903.34
       1570255.5      6798098.17      1570203.95      6798477.57
      1570007.98      6798646.34       1570043.9      6798798.06
      1569760.74      6799085.48      1569712.56        6799188.
      1569753.33      6799281.95      1569655.66      6799398.65
      1569665.53      6799527.53      1569456.26      6799541.48
      1569388.96      6799637.69      1569298.29      6799597.16
      1568968.33      6799974.61      1568804.69      6800030.78
      1568418.32      6799601.37      1568248.53       6799580.3
      1568011.73      6799347.15      1567715.47      6799437.47
      1567453.45      6799191.75        1567205.        6799188.

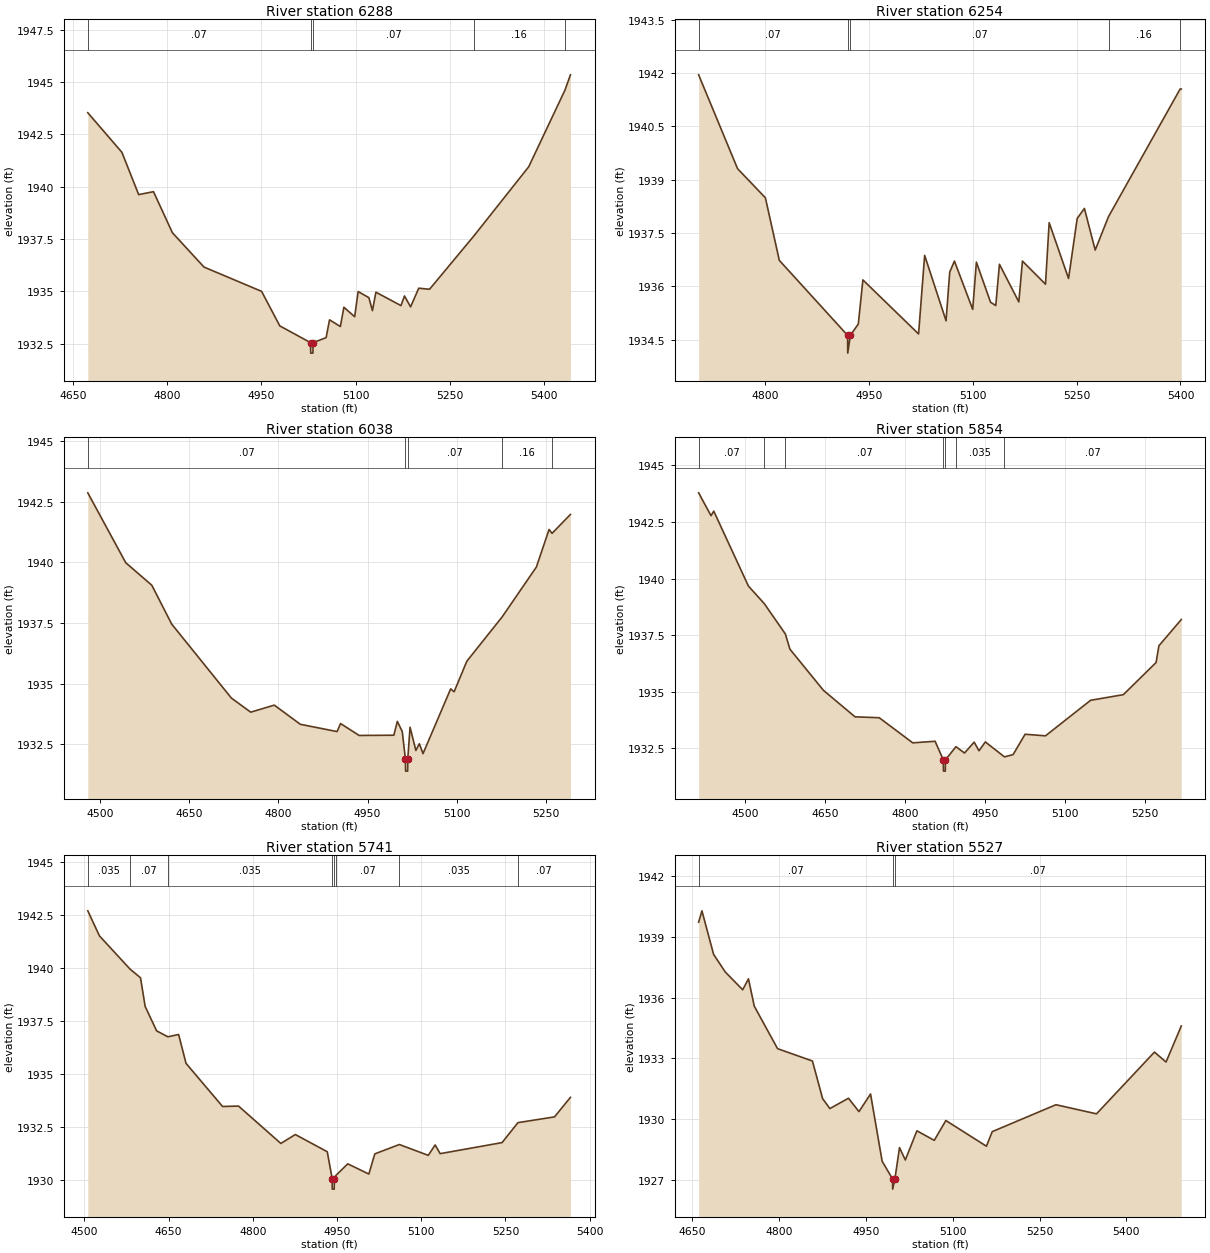
Type RM Length L Ch R = 1 ,6288    ,34,34,34
BEGIN DESCRIPTION:
Elm 01 11 6170.278
END DESCRIPTION:
XS GIS Cut Line= 3
      1569831.03      6797161.67      1570155.62      6797127.38
        1570555.        6796938.
#Sta/Elev= 30
  4673.6 1943.53  4727.9 1941.64  4754.6 1939.62  4778.2 1939.76  4808.3  1937.8
  4858.6 1936.16  4950.3    1935  4979.3 1933.35  5028.3 1932.55  5028.5 1932.05
    5032 1932.05  5032.3 1932.55    5053 1932.79  5058.5 1933.64  5075.7 1933.32
  5081.3 1934.24  5098.5 1933.79    5104 1934.99  5121.1  1934.7  5126.8 1934.08
  5132.3 1934.96  5172.2 1934.32  5177.8 1934.78  5187.5 1934.26  5200.5 1935.15
  5217.7  1935.1  5288.1 1937.64  5375.6 1940.95  5433.3 1944.61    5442 1945.34
#Mann= 5 ,-1 , 0
  4673.6     .07       0  5028.3     .07       0  5032.3     .07       0
  5288.1     .16       0  5433.3     .07       0
Bank Sta=5028.3,5032.3
XS Rating Curve= 0 ,0
Exp/Cntr=0.3,0.1

Type RM Length L Ch R = 1 ,6254    ,216,216,216
BEGIN DESCRIPTION:
Elm 01 11 12.0
END DESCRIPTION:
XS GIS Cut Line= 3
      1569879.12      6797187.05      1570203.72      6797152.76
      1570559.14       6797047.8
#Sta/Elev= 30
  4704.2 1941.95  4760.4 1939.31  4800.6 1938.49  4820.7 1936.73  4919.3 1934.62
  4919.5 1934.12  4923.3 1934.62  4934.8 1934.94  4941.4 1936.18  5021.8 1934.66
  5030.6 1936.87  5061.5 1935.03  5066.8  1936.4  5073.6 1936.71    5100 1935.35
  5105.3 1936.68  5125.8 1935.55  5133.3 1935.46  5138.6 1936.62  5166.6 1935.56
  5171.8 1936.71  5205.1 1936.06  5210.4 1937.79  5238.4 1936.22  5250.9 1937.91
  5261.3 1938.19  5276.9 1937.02  5296.1 1937.96  5399.5 1941.55  5401.2 1941.55
#Mann= 5 ,-1 , 0
  4704.2     .07       0  4919.3     .07       0  4923.3     .07       0
  5296.1     .16       0  5399.5     .07       0
Bank Sta=4919.3,4923.3
XS Rating Curve= 0 ,0
Exp/Cntr=0.3,0.1

Type RM Length L Ch R = 1 ,6038    ,184,184,184
BEGIN DESCRIPTION:
Elm 01 11 6038.06
END DESCRIPTION:
XS GIS Cut Line= 3
      1569851.98      6797184.13      1570219.99      6797291.76
      1570588.06        6797073.
#Sta/Elev= 30
  4479.6 1942.87  4543.4 1939.99  4587.3 1939.06  4620.7 1937.46  4721.1 1934.41
  4753.6 1933.83  4793.2 1934.12    4837 1933.33  4898.8 1933.03  4904.7 1933.36
  4935.9 1932.87  4994.3 1932.88  5000.1 1933.45  5008.4 1933.03  5013.7  1931.9
    5014  1931.4  5017.5  1931.4  5017.7  1931.9  5021.5 1933.21  5031.3 1932.25
  5037.1 1932.53  5043.3 1932.12  5089.8 1934.79  5095.6 1934.67    5117 1935.93
  5176.5 1937.76  5233.9 1939.81  5255.3 1941.36  5260.3  1941.2  5291.2 1941.98
#Mann= 5 ,-1 , 0
  4479.6     .07       0  5013.7     .07       0  5017.7     .07       0
  5176.5     .16       0  5260.3     .07       0
Bank Sta=5013.7,5017.7
XS Rating Curve= 0 ,0
Exp/Cntr=0.3,0.1

Type RM Length L Ch R = 1 ,5854    ,113,113,113
BEGIN DESCRIPTION:
Elm 01 11 5854.04
END DESCRIPTION:
XS GIS Cut Line= 3
      1569841.49      6797204.94      1570397.08      6797378.56
      1570716.48      6797430.64
#Sta/Elev= 30
  4412.5 1943.79  4435.7 1942.78  4440.9 1942.98  4505.9 1939.67  4535.8 1938.89
  4575.3 1937.55  4583.8 1936.88  4646.7 1935.06    4706 1933.89  4751.4 1933.85
  4814.3 1932.74  4856.2 1932.81  4871.6 1931.99  4871.9 1931.49  4875.4 1931.49
  4875.6 1931.99  4895.4 1932.57  4911.4 1932.29  4929.5 1932.77  4938.6 1932.39
  4950.5 1932.78  4986.4 1932.12  5002.6 1932.22  5025.1 1933.12  5063.4 1933.05
    5148 1934.62  5209.5 1934.87  5270.9 1936.29  5276.2 1937.03  5318.2 1938.19
#Mann= 7 ,-1 , 0
  4412.5     .07       0  4535.8    .035       0  4575.3     .07       0
  4871.6     .07       0  4875.6     .07       0  4895.4    .035       0
  4986.4     .07       0
Bank Sta=4871.6,4875.6
XS Rating Curve= 0 ,0
Exp/Cntr=0.3,0.1

Type RM Length L Ch R = 1 ,5741    ,214,214,214
BEGIN DESCRIPTION:
Elm 01 11 5696.46
END DESCRIPTION:
XS GIS Cut Line= 3
      1569856.65       6797318.3      1570149.92      6797401.27
      1570674.27      6797583.22
#Sta/Elev= 30
  4506.1 1942.69  4526.9 1941.51  4581.6 1939.94    4600 1939.54  4608.3 1938.19
  4628.7 1937.04  4648.8 1936.76  4667.9 1936.87  4681.1 1935.51  4746.2 1933.48
  4774.6  1933.5    4850 1931.74  4875.8 1932.16  4932.7 1931.35  4941.4 1930.09
  4941.6 1929.59  4945.1 1929.59  4945.4 1930.09  4948.3 1930.24  4969.2 1930.78
  5006.8  1930.3  5017.4 1931.25  5061.1 1931.69  5112.6 1931.18  5124.9 1931.67
  5133.8 1931.26  5244.1 1931.78  5272.4 1932.72  5337.5 1932.99  5365.9 1933.91
#Mann= 8 ,-1 , 0
  4506.1    .035       0  4581.6     .07       0  4648.8    .035       0
  4941.4     .07       0  4945.4    .035       0  4948.3     .07       0
  5061.1    .035       0  5272.4     .07       0
Bank Sta=4941.4,4945.4
XS Rating Curve= 0 ,0
Exp/Cntr=0.3,0.1

Type RM Length L Ch R = 1 ,5527    ,200,200,200
BEGIN DESCRIPTION:
Elm 01 11 5442.33
END DESCRIPTION:
XS GIS Cut Line= 3
      1569869.32      6797604.26      1570126.95      6797626.64
      1570701.28      6797635.48
#Sta/Elev= 30
  4661.7 1939.73  4667.4 1940.29  4687.5 1938.14  4707.6 1937.27  4737.7 1936.39
  4747.7 1936.93  4757.7 1935.58  4797.9 1933.48  4858.1 1932.87  4875.7 1931.01
  4888.2 1930.52  4920.3 1931.03  4938.4 1930.37  4958.4 1931.24  4978.4 1927.92
  4996.4 1927.04  4996.6 1926.54  5000.4 1927.04  5008.4 1928.59  5018.4 1927.98
  5038.4 1929.42  5068.4 1928.95  5088.4 1929.93  5158.4 1928.66  5168.4 1929.38
  5278.4 1930.71  5348.4 1930.26  5448.4 1933.31  5468.4 1932.82  5494.7  1934.6
#Mann= 3 ,-1 , 0
  4661.7     .07       0  4996.4     .07       0  5000.4     .07       0
Bank Sta=4996.4,5000.4
XS Rating Curve= 0 ,0
Exp/Cntr=0.3,0.1

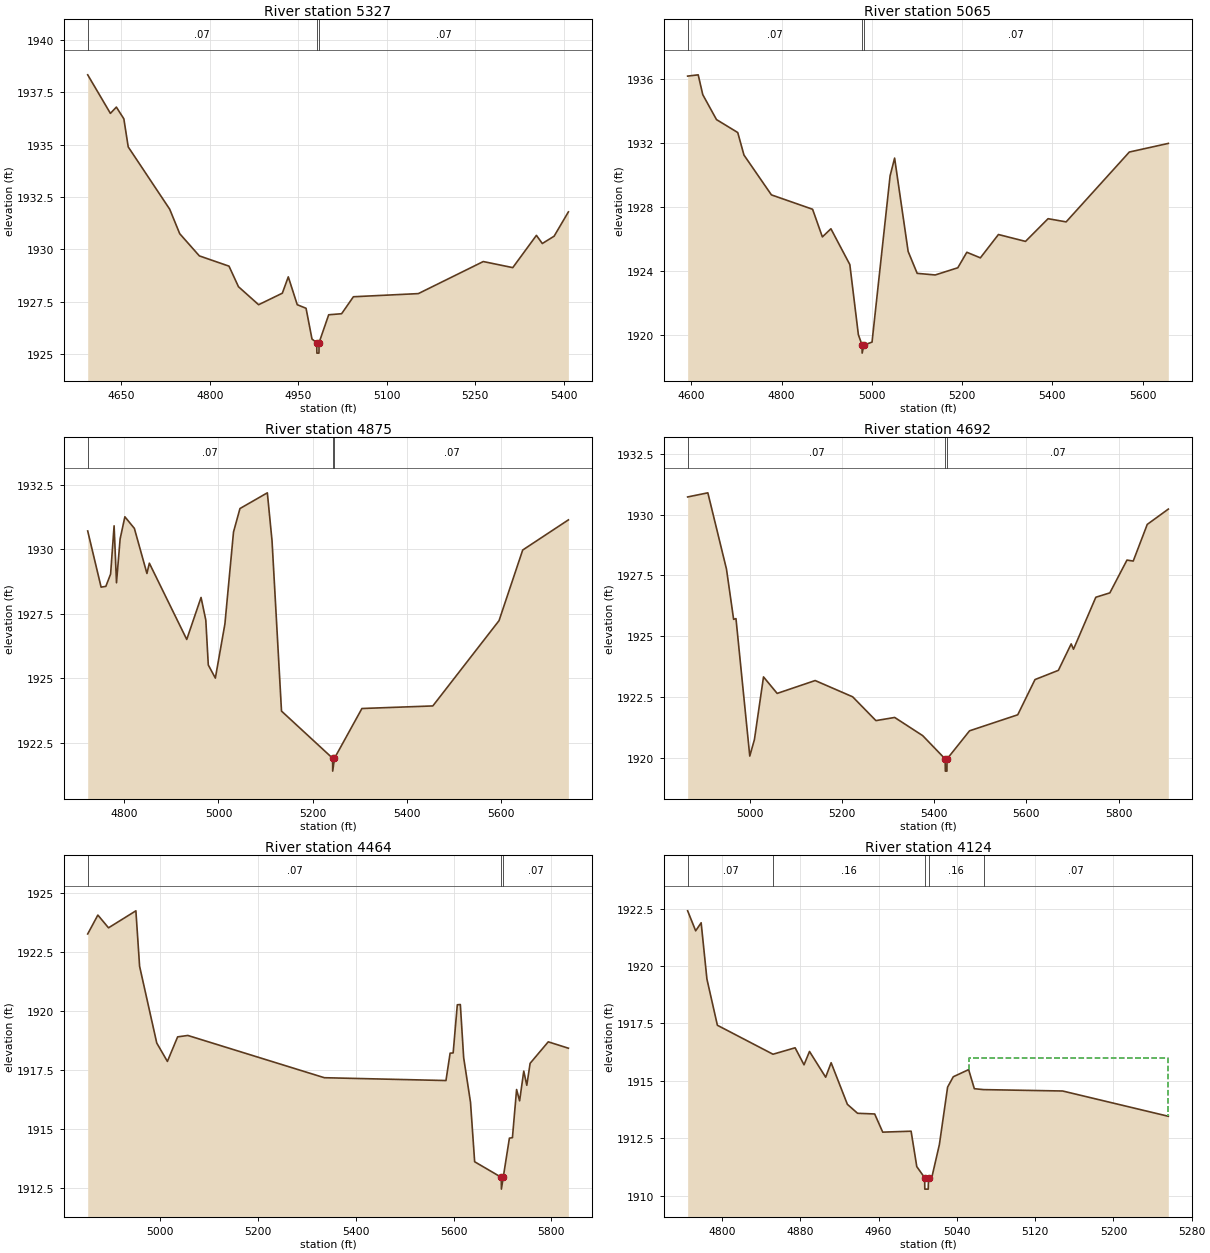
Type RM Length L Ch R = 1 ,5327    ,262,262,262
BEGIN DESCRIPTION:
Elm 01 11 5326.53
END DESCRIPTION:
XS GIS Cut Line= 3
      1569886.68      6797757.03      1570296.38       6797798.7
      1570699.19      6797781.34
#Sta/Elev= 30
    4593 1938.33  4631.5 1936.49  4641.6 1936.79  4654.3 1936.23  4661.7 1934.89
    4732 1931.92    4749 1930.75  4782.3 1929.69  4832.6  1929.2  4848.6 1928.22
  4882.8 1927.36    4923 1927.91  4933.1 1928.69  4948.3 1927.36  4963.2 1927.19
  4973.3 1925.72  4981.3 1925.55  4981.6 1925.05  4985.1 1925.05  4985.3 1925.55
  5001.6 1926.88  5023.5 1926.93  5043.5 1927.74  5153.6 1927.89  5263.7 1929.42
  5313.7 1929.13  5353.8 1930.67  5363.8 1930.28  5383.8 1930.63    5408 1931.79
#Mann= 3 ,-1 , 0
    4593     .07       0  4981.3     .07       0  4985.3     .07       0
Bank Sta=4981.3,4985.3
XS Rating Curve= 0 ,0
Exp/Cntr=0.3,0.1

Type RM Length L Ch R = 1 ,5065    ,190,190,190
BEGIN DESCRIPTION:
Elm 01 11 5065.1
END DESCRIPTION:
XS GIS Cut Line= 3
      1569851.92      6797944.53      1570247.77      6798010.51
      1570911.36      6798008.74
#Sta/Elev= 30
  4591.9  1936.2  4615.3 1936.28  4625.4 1935.04  4655.8 1933.48  4702.9 1932.67
  4716.7 1931.26  4777.5 1928.77  4868.7 1927.87  4890.4 1926.14  4909.3 1926.65
  4951.2 1924.41  4970.1 1920.03  4978.3 1919.37  4978.5 1918.87  4982.3 1919.37
  5000.4 1919.56  5040.4 1929.96  5050.4 1931.07  5080.4 1925.23  5100.4 1923.86
  5140.4 1923.76  5190.4 1924.21  5210.4 1925.18  5240.4 1924.83  5280.4 1926.29
  5340.4 1925.86  5390.4 1927.28  5430.4 1927.08  5570.4 1931.45  5656.8 1931.99
#Mann= 3 ,-1 , 0
  4591.9     .07       0  4978.3     .07       0  4982.3     .07       0
Bank Sta=4978.3,4982.3
XS Rating Curve= 0 ,0
Exp/Cntr=0.3,0.1

Type RM Length L Ch R = 1 ,4875    ,183,183,183
BEGIN DESCRIPTION:
Elm 01 11 7.0
END DESCRIPTION:
XS GIS Cut Line= 5
       1569936.8       6798144.5      1570132.74      6798173.27
        1570246.      6798192.37      1570297.07      6798159.13
      1570941.67      6798095.09
#Sta/Elev= 30
  4722.1 1930.71  4750.6 1928.53  4760.7 1928.56  4770.8 1929.04  4778.2 1930.91
  4783.3  1928.7    4791  1930.4  4801.1 1931.26  4821.3 1930.81    4848 1929.06
  4853.1 1929.46  4932.6  1926.5    4963 1928.13  4973.1 1927.25  4978.4 1925.51
  4993.4    1925  5013.7  1927.1    5032 1930.67  5045.7 1931.58  5103.9 1932.19
  5113.9 1930.32    5134 1923.72  5242.6 1921.89  5242.8 1921.39  5246.6 1921.89
  5304.9 1923.82  5455.6 1923.92  5596.3 1927.23  5646.6 1929.97  5743.7 1931.14
#Mann= 3 ,-1 , 0
  4722.1     .07       0  5242.6     .07       0  5246.6     .07       0
Bank Sta=5242.6,5246.6
XS Rating Curve= 0 ,0
Exp/Cntr=0.3,0.1

Type RM Length L Ch R = 1 ,4692    ,228,228,228
BEGIN DESCRIPTION:
Elm 01 11 4810.27
END DESCRIPTION:
XS GIS Cut Line= 3
       1570071.7      6798348.46      1570267.58      6798377.22
      1571100.04      6798517.65
#Sta/Elev= 30
  4865.7 1930.73  4909.5  1930.9  4949.9 1927.76  4965.4 1925.69  4970.5 1925.72
  5000.4 1920.06  5010.5 1920.74  5030.2 1923.32  5059.8 1922.64  5142.2 1923.17
  5223.5  1922.5  5273.9 1921.52  5314.6 1921.65  5375.4  1920.9  5424.1 1919.94
  5424.4 1919.44  5427.9 1919.44  5428.1 1919.94  5476.9  1921.1  5581.4 1921.76
  5618.8 1923.21  5669.5 1923.59  5697.3 1924.68  5702.3 1924.46  5750.7  1926.6
  5781.1 1926.78  5818.2 1928.13  5831.8 1928.09  5862.2  1929.6  5907.9 1930.23
#Mann= 3 ,-1 , 0
  4865.7     .07       0  5424.1     .07       0  5428.1     .07       0
Bank Sta=5424.1,5428.1
XS Rating Curve= 0 ,0
Exp/Cntr=0.3,0.1

Type RM Length L Ch R = 1 ,4464    ,340,340,340
BEGIN DESCRIPTION:
Elm 01 11 4508.88
END DESCRIPTION:
XS GIS Cut Line= 3
      1570028.67       6798454.6      1570234.09      6798687.79
      1570778.32      6799083.42
#Sta/Elev= 30
  4851.4 1923.25  4872.2 1924.05    4894 1923.51    4950 1924.23  4957.6 1921.88
  4992.7 1918.63  5014.5 1917.85  5035.4 1918.89  5056.3 1918.95  5335.6 1917.16
  5584.5 1917.04    5593  1918.2  5599.2 1918.21  5607.7 1920.25  5613.9 1920.26
  5620.7 1918.01  5634.7 1916.12  5643.2  1913.6  5697.7 1912.94  5697.9 1912.44
  5701.7 1912.94  5714.3  1914.6  5720.5 1914.62    5729 1916.66  5735.2 1916.18
  5743.7 1917.44  5749.9 1916.84  5756.7 1917.77  5793.8 1918.68    5835 1918.41
#Mann= 3 ,-1 , 0
  4851.4     .07       0  5697.7     .07       0  5701.7     .07       0
Bank Sta=5697.7,5701.7
XS Rating Curve= 0 ,0
Exp/Cntr=0.3,0.1

Type RM Length L Ch R = 1 ,4124    ,200,200,200
BEGIN DESCRIPTION:
Elm 01 11 4157.68
END DESCRIPTION:
XS GIS Cut Line= 3
      1569893.73      6798630.51      1569974.47      6798786.39
      1570247.21      6798945.09
#Sta/Elev= 30
    4765  1922.4  4773.2 1921.53  4778.8 1921.88  4784.7 1919.43  4795.4 1917.42
  4852.2 1916.16  4874.8 1916.44  4883.9  1915.7  4889.5 1916.28    4906 1915.16
  4911.6 1915.79  4928.2 1913.98  4938.6 1913.59  4956.1 1913.56  4964.3 1912.77
  4993.3 1912.81  4999.1 1911.27  5007.1 1910.79  5007.3 1910.29  5010.8 1910.29
  5011.1 1910.79  5014.9 1910.88  5022.2 1912.23  5030.6 1914.73  5036.4 1915.18
  5052.1 1915.49  5057.9 1914.66  5067.4 1914.62  5148.1 1914.56  5256.1 1913.46
#Mann= 5 ,-1 , 0
    4765     .07       0  4852.2     .16       0  5007.1     .07       0
  5011.1     .16       0  5067.4     .07       0
#XS Ineff= 2 , 0
       0                    5052       0    1916
Permanent Ineff=
       F       F
Bank Sta=5007.1,5011.1
XS Rating Curve= 0 ,0
Exp/Cntr=0.3,0.1

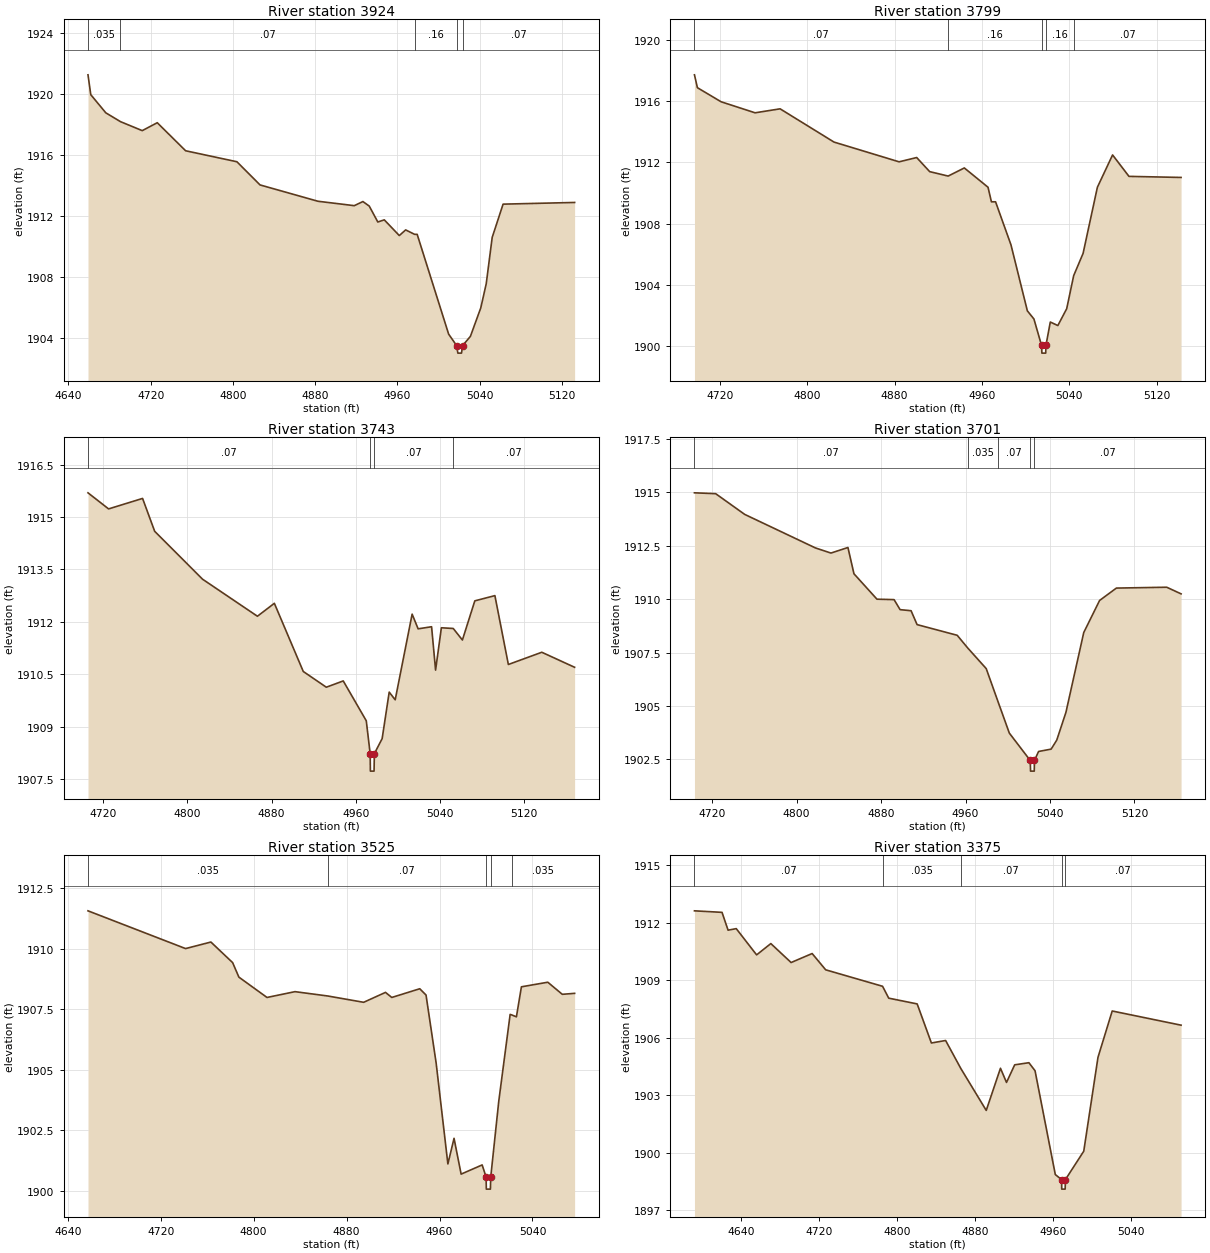
Type RM Length L Ch R = 1 ,3924    ,125,125,125
BEGIN DESCRIPTION:
Elm 01 11 4005.1
END DESCRIPTION:
XS GIS Cut Line= 3
      1569608.91      6798760.53      1569862.15      6798949.84
      1570010.81      6799001.34
#Sta/Elev= 30
    4659 1921.27  4661.7 1919.97  4676.3 1918.78  4690.6  1918.2  4711.8 1917.61
  4726.4 1918.13    4754 1916.29  4803.9 1915.57  4826.4 1914.05  4882.7 1912.98
  4918.1 1912.69  4926.5 1912.96  4932.7 1912.66    4941 1911.62  4947.3 1911.76
  4961.9 1910.73  4968.1  1911.1  4976.8 1910.81  4979.3 1910.81  5009.9 1904.27
  5017.6 1903.52  5018.9 1903.02  5022.4 1903.02  5023.6 1903.52  5031.1 1904.12
  5041.2 1905.99  5046.5 1907.57  5052.3 1910.61  5062.9 1912.79  5132.5  1912.9
#Mann= 5 ,-1 , 0
    4659    .035       0  4690.6     .07       0  4976.8     .16       0
  5017.6     .07       0  5023.6     .07       0
Bank Sta=5017.6,5023.6
XS Rating Curve= 0 ,0
Exp/Cntr=0.3,0.1

Type RM Length L Ch R = 1 ,3799    ,56,56,56
BEGIN DESCRIPTION:
Elm 01 11 3836.93
END DESCRIPTION:
XS GIS Cut Line= 3
      1569546.36      6798892.44      1569785.37      6799023.97
      1569928.62      6799120.23
#Sta/Elev= 30
  4696.8 1917.71  4699.5 1916.87  4721.2 1915.95  4752.3 1915.23  4775.2 1915.49
  4824.5 1913.32  4884.1 1912.03  4900.2 1912.31  4912.1 1911.39    4929  1911.1
  4943.8 1911.63  4965.5 1910.37  4968.6 1909.42  4972.4 1909.42  4986.5 1906.61
  5001.5  1902.3  5007.5 1901.77  5014.5 1900.04  5014.8 1899.54  5018.3 1899.54
  5018.5 1900.04  5022.5 1901.57  5029.4 1901.34  5037.5 1902.44  5043.9  1904.6
  5052.5 1906.05  5065.6 1910.37  5079.5 1912.48  5094.5 1911.08  5142.2 1911.01
#Mann= 5 ,-1 , 0
  4696.8     .07       0    4929     .16       0  5014.5     .07       0
  5018.5     .16       0  5043.9     .07       0
Bank Sta=5014.5,5018.5
XS Rating Curve= 0 ,0
Exp/Cntr=0.3,0.1

Type RM Length L Ch R = 1 ,3743    ,42,42,42
BEGIN DESCRIPTION:
Elm 01 11 4.0
END DESCRIPTION:
XS GIS Cut Line= 3
      1569509.35      6798935.51      1569796.19       6799091.8
      1569924.41      6799137.28
#Sta/Elev= 30
  4705.4 1915.69    4725 1915.23  4757.3 1915.53  4768.8 1914.59  4814.3 1913.22
  4866.5 1912.16  4882.6 1912.53  4910.1 1910.58    4932 1910.13  4948.1 1910.31
    4970 1909.17  4973.7 1908.23  4973.9 1907.73  4977.4 1907.73  4977.7 1908.23
  4985.1 1908.66  4991.8 1909.99  4997.5 1909.77  5013.6 1912.22  5019.3  1911.8
  5032.1 1911.86  5035.9 1910.62  5041.4 1911.83  5052.7 1911.81  5061.4 1911.48
  5073.2  1912.6  5092.3 1912.75  5105.1 1910.78  5136.9 1911.13  5168.1  1910.7
#Mann= 4 ,-1 , 0
  4705.4     .07       0  4973.7     .07       0  4977.7     .07       0
  5052.7     .07       0
Bank Sta=4973.7,4977.7
XS Rating Curve= 0 ,0
Exp/Cntr=0.3,0.1

Type RM Length L Ch R = 1 ,3701    ,176,176,176
BEGIN DESCRIPTION:
Elm 01 11 3709.21
END DESCRIPTION:
XS GIS Cut Line= 3
      1569494.33      6798972.33      1569781.11      6799128.58
      1569907.79      6799173.52
#Sta/Elev= 30
  4703.2 1914.98  4723.3 1914.94  4750.8 1913.97  4817.8  1912.4  4832.5 1912.16
  4848.6 1912.42  4854.3 1911.19  4876.1    1910  4892.3 1909.98    4898 1909.51
  4908.4 1909.46  4914.1 1908.81  4952.1 1908.31    4962 1907.72  4979.6 1906.75
  4990.8  1905.2  5001.5 1903.73  5021.3 1902.45  5021.6 1901.95  5025.1 1901.95
  5025.3 1902.45  5029.2 1902.87  5041.1 1902.98  5046.4  1903.4  5055.1  1904.7
    5072 1908.44    5087 1909.94  5102.9 1910.52  5150.6 1910.56  5164.2 1910.25
#Mann= 5 ,-1 , 0
  4703.2     .07       0    4962    .035       0  4990.8     .07       0
  5021.3     .07       0  5025.3     .07       0
Bank Sta=5021.3,5025.3
XS Rating Curve= 0 ,0
Exp/Cntr=0.3,0.1

Type RM Length L Ch R = 1 ,3525    ,150,150,150
BEGIN DESCRIPTION:
Elm 01 11 3.0
END DESCRIPTION:
XS GIS Cut Line= 3
      1569437.07       6799135.4      1569786.25       6799276.2
      1569827.47      6799286.16
#Sta/Elev= 30
  4657.4 1911.56  4741.4    1910  4763.2 1910.27  4781.9 1909.42  4787.3 1908.82
  4811.5 1907.98  4835.6 1908.22  4863.9 1908.04  4894.7 1907.78  4913.5 1908.19
  4918.9 1907.98    4943 1908.34  4948.4 1908.08  4957.1 1905.27  4967.2  1901.1
  4972.5 1902.16  4978.6 1900.68  4996.7 1901.06  5000.1 1900.56  5000.3 1900.06
  5003.8 1900.06  5004.1 1900.56    5011 1903.69  5020.8 1907.28  5022.1 1907.26
  5026.2 1907.18  5030.5 1908.42  5053.2 1908.61  5065.7 1908.11  5076.3 1908.15
#Mann= 5 ,-1 , 0
  4657.4    .035       0  4863.9     .07       0  5000.1     .07       0
  5004.1     .07       0  5022.1    .035       0
Bank Sta=5000.1,5004.1
XS Rating Curve= 0 ,0
Exp/Cntr=0.3,0.1

Type RM Length L Ch R = 1 ,3375    ,152,152,152
BEGIN DESCRIPTION:
Elm 01 11 3539.08
END DESCRIPTION:
XS GIS Cut Line= 3
      1569338.06      6799135.52      1569685.58      6799393.76
      1569751.58       6799385.3
#Sta/Elev= 30
  4592.3 1912.62  4620.6 1912.54  4626.8 1911.61  4635.2 1911.69  4656.1 1910.32
  4670.7 1910.91  4691.5 1909.92  4713.1 1910.39    4727 1909.54  4785.4 1908.68
  4791.7 1908.06  4820.9 1907.76  4835.5 1905.72  4850.1 1905.85  4865.7 1904.39
  4891.8  1902.2  4906.4  1904.4  4912.6 1903.66    4921 1904.58  4935.6 1904.69
  4941.9 1904.27  4962.7 1898.85  4969.1 1898.59  4969.3 1898.09  4972.8 1898.09
  4973.1 1898.59  4991.9 1900.07  5006.5 1904.97  5021.1 1907.39  5091.8 1906.65
#Mann= 5 ,-1 , 0
  4592.3     .07       0  4785.4    .035       0  4865.7     .07       0
  4969.1     .07       0  4973.1     .07       0
Bank Sta=4969.1,4973.1
XS Rating Curve= 0 ,0
Exp/Cntr=0.3,0.1

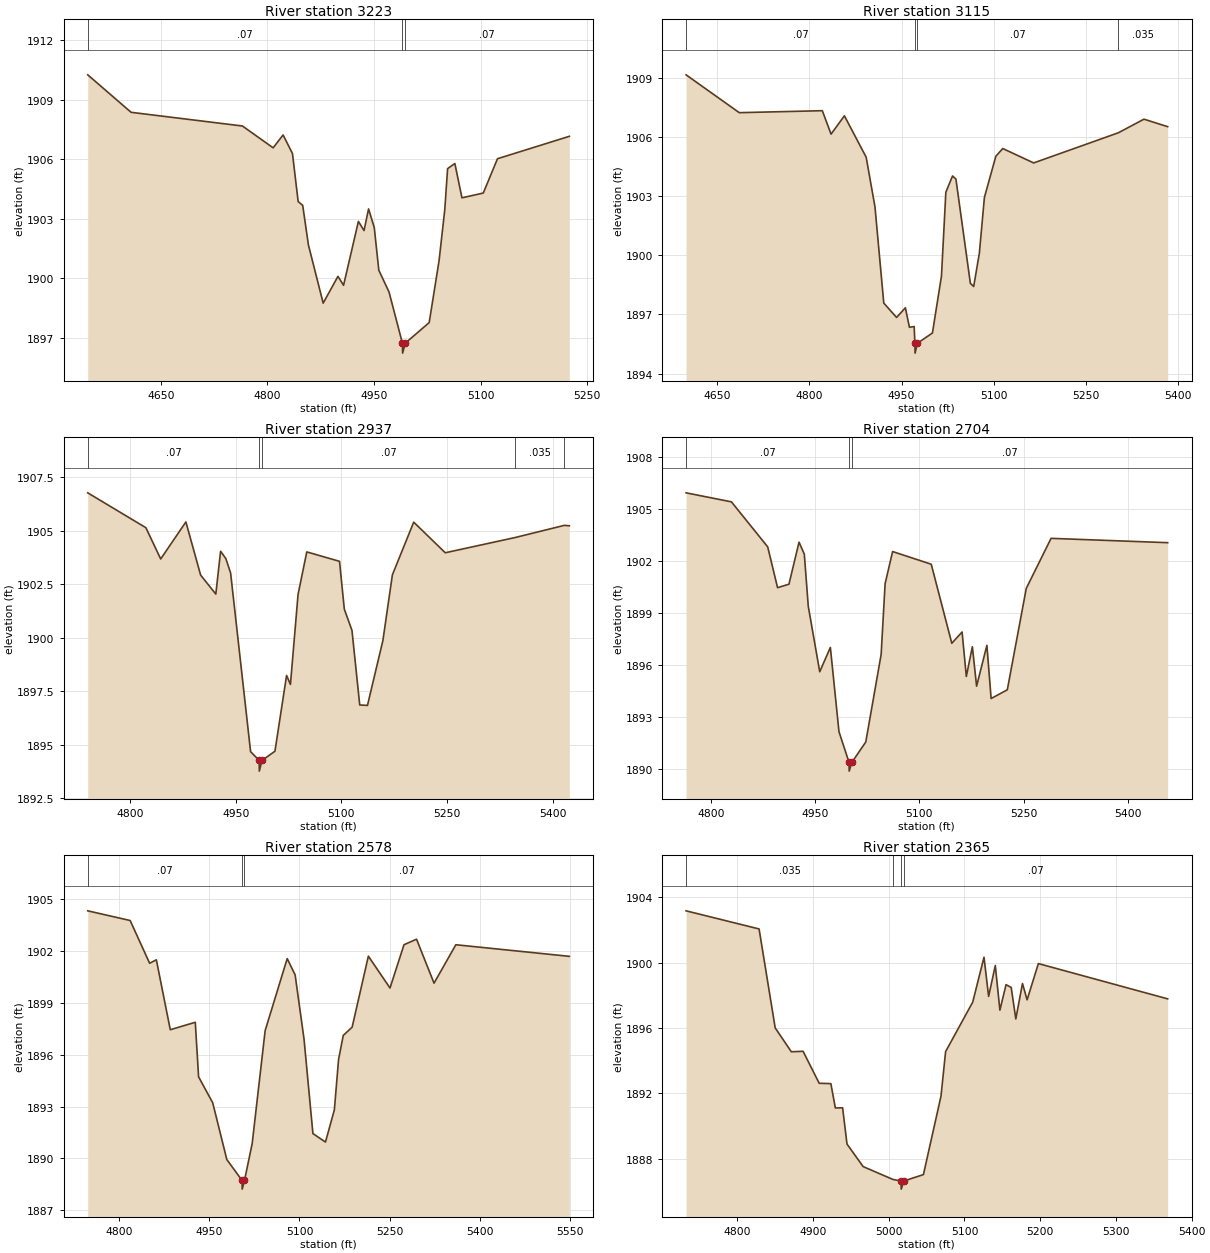
Type RM Length L Ch R = 1 ,3223    ,108,108,108
BEGIN DESCRIPTION:
Elm 01 11 3348.31
END DESCRIPTION:
XS GIS Cut Line= 3
      1569331.13       6799225.8      1569726.29      6799544.87
      1569896.08      6799542.79
#Sta/Elev= 30
  4547.1 1910.26  4608.1 1908.37  4764.8 1907.68    4808 1906.58    4822 1907.23
  4835.2 1906.29  4843.2 1903.87  4849.6 1903.68  4857.6 1901.69  4878.4 1898.75
  4899.2  1900.1  4907.1 1899.65    4928 1902.87  4935.9 1902.41  4942.3  1903.5
  4950.3 1902.56  4956.7 1900.41  4971.1 1899.31  4989.9 1896.73  4990.2 1896.23
  4993.9 1896.73  5027.6 1897.77  5041.5 1900.89  5049.5 1903.45  5053.5 1905.53
  5063.7 1905.79  5073.7 1904.06  5103.7  1904.3  5123.7 1906.03  5224.8 1907.16
#Mann= 3 ,-1 , 0
  4547.1     .07       0  4989.9     .07       0  4993.9     .07       0
Bank Sta=4989.9,4993.9
XS Rating Curve= 0 ,0
Exp/Cntr=0.3,0.1

Type RM Length L Ch R = 1 ,3115    ,178,178,178
BEGIN DESCRIPTION:
Elm 01 11 3117.71
END DESCRIPTION:
XS GIS Cut Line= 4
      1569289.45      6799270.94      1569574.98      6799515.36
      1569619.53      6799618.07      1569907.79      6799681.19
#Sta/Elev= 30
  4599.6 1909.16  4686.1 1907.24  4821.1 1907.34  4835.3 1906.15    4857 1907.08
  4892.4 1904.98  4906.7 1902.46    4921 1897.58  4941.8 1896.85  4956.1 1897.34
  4962.7 1896.35  4970.4 1896.39  4971.6 1895.54  4971.9 1895.04  4975.6 1895.54
  5000.1 1896.06  5014.8 1898.95  5021.9  1903.2  5032.8 1904.03  5038.3 1903.87
  5061.8 1898.58  5067.2 1898.42  5076.4 1900.11  5084.6 1902.94  5103.2 1905.03
  5114.5 1905.42  5164.7 1904.69  5302.4 1906.22    5344 1906.91  5382.5 1906.53
#Mann= 4 ,-1 , 0
  4599.6     .07       0  4971.6     .07       0  4975.6     .07       0
  5302.4    .035       0
Bank Sta=4971.6,4975.6
XS Rating Curve= 0 ,0
Exp/Cntr=0.3,0.1

Type RM Length L Ch R = 1 ,2937    ,233,233,233
BEGIN DESCRIPTION:
Elm 01 11 2937.08
END DESCRIPTION:
XS GIS Cut Line= 3
       1569244.3      6799382.03      1569417.91      6799573.01
      1569806.82      6799746.63
#Sta/Elev= 30
  4739.8 1906.77  4822.4 1905.14  4843.4 1903.68  4879.2 1905.41  4900.1 1902.93
  4921.7 1902.04  4928.5 1904.04  4935.9  1903.7  4942.7 1903.03  4971.1 1894.68
  4983.3 1894.27  4983.5 1893.77  4987.3 1894.27  5005.7  1894.7  5022.2 1898.24
  5027.7 1897.82  5038.5 1902.02  5050.9 1904.01  5097.4 1903.57  5104.2 1901.34
  5115.1 1900.34  5126.1 1896.86  5137.1 1896.84    5159 1899.87  5172.5 1902.94
  5202.8  1905.4  5247.6 1903.97  5346.6 1904.68  5416.7 1905.25  5423.8 1905.23
#Mann= 5 ,-1 , 0
  4739.8     .07       0  4983.3     .07       0  4987.3     .07       0
  5346.6    .035       0  5416.7     .07       0
Bank Sta=4983.3,4987.3
XS Rating Curve= 0 ,0
Exp/Cntr=0.3,0.1

Type RM Length L Ch R = 1 ,2704    ,126,126,126
BEGIN DESCRIPTION:
Elm 01 11 2702.83
END DESCRIPTION:
XS GIS Cut Line= 3
      1569150.57      6799423.74      1569297.69      6799706.87
      1569603.86      6799921.87
#Sta/Elev= 30
  4764.3 1905.92  4829.6  1905.4  4881.8 1902.81    4896 1900.46  4912.4 1900.66
  4926.9 1903.08  4934.5 1902.39  4940.2 1899.39  4956.7 1895.62    4972 1897.02
  4984.4 1892.17  4998.9  1890.4  4999.1  1889.9  5002.9  1890.4    5023 1891.58
  5045.1 1896.62  5050.8 1900.69  5061.6 1902.54  5117.2 1901.81  5146.8 1897.26
  5161.6 1897.91  5167.7 1895.35  5176.4 1897.06  5182.5 1894.79  5197.3 1897.14
  5203.4 1894.08  5226.7 1894.58    5254 1900.42  5289.7  1903.3  5457.5 1903.05
#Mann= 3 ,-1 , 0
  4764.3     .07       0  4998.9     .07       0  5002.9     .07       0
Bank Sta=4998.9,5002.9
XS Rating Curve= 0 ,0
Exp/Cntr=0.3,0.1

Type RM Length L Ch R = 1 ,2578    ,213,213,213
BEGIN DESCRIPTION:
Elm 01 11 2577.61
END DESCRIPTION:
XS GIS Cut Line= 3
      1569067.21      6799493.14      1569164.44      6799718.84
      1569619.31      6800038.29
#Sta/Elev= 30
  4747.6 1904.31  4818.2 1903.75  4850.6 1901.28  4861.8 1901.48    4885 1897.44
  4926.6 1897.87  4932.1 1894.72  4955.6 1893.22  4979.1 1889.94  5004.5 1888.73
  5004.7 1888.23  5008.5 1888.73  5021.3 1890.86  5042.9 1897.39  5079.6 1901.55
  5092.8 1900.61  5107.6  1896.9  5122.4 1891.44  5143.3 1890.95  5158.1 1892.81
  5165.1 1895.72  5172.9 1897.11  5187.7 1897.59  5214.7 1901.69  5250.7 1899.85
    5274 1902.35  5294.9 1902.67    5324 1900.13  5360.3 1902.35  5549.2 1901.68
#Mann= 3 ,-1 , 0
  4747.6     .07       0  5004.5     .07       0  5008.5     .07       0
Bank Sta=5004.5,5008.5
XS Rating Curve= 0 ,0
Exp/Cntr=0.3,0.1

Type RM Length L Ch R = 1 ,2365    ,137,137,137
BEGIN DESCRIPTION:
Elm 01 11 2377.74
END DESCRIPTION:
XS GIS Cut Line= 3
      1568909.34      6799661.44       1569056.8      6799902.87
       1569256.3      6800194.09
#Sta/Elev= 30
  4732.4 1903.18  4828.8 1902.07  4850.1 1896.01  4871.4 1894.55  4886.9 1894.58
  4908.2 1892.62  4923.6  1892.6  4929.5 1891.11  4939.1 1891.12  4944.9  1888.9
  4966.2 1887.52  5005.7 1886.73  5016.2 1886.64  5016.5 1886.14  5020.2 1886.64
  5045.8 1887.03    5069 1891.83  5075.1 1894.56  5110.9 1897.59  5125.8 1900.34
  5131.9 1897.94  5140.7 1899.83  5146.8  1897.1  5154.9 1898.66  5161.7 1898.49
  5167.8 1896.56  5176.6 1898.73  5182.7 1897.73  5197.6 1899.95  5368.3 1897.79
#Mann= 4 ,-1 , 0
  4732.4    .035       0  5005.7     .07       0  5016.2    .035       0
  5020.2     .07       0
Bank Sta=5016.2,5020.2
XS Rating Curve= 0 ,0
Exp/Cntr=0.3,0.1

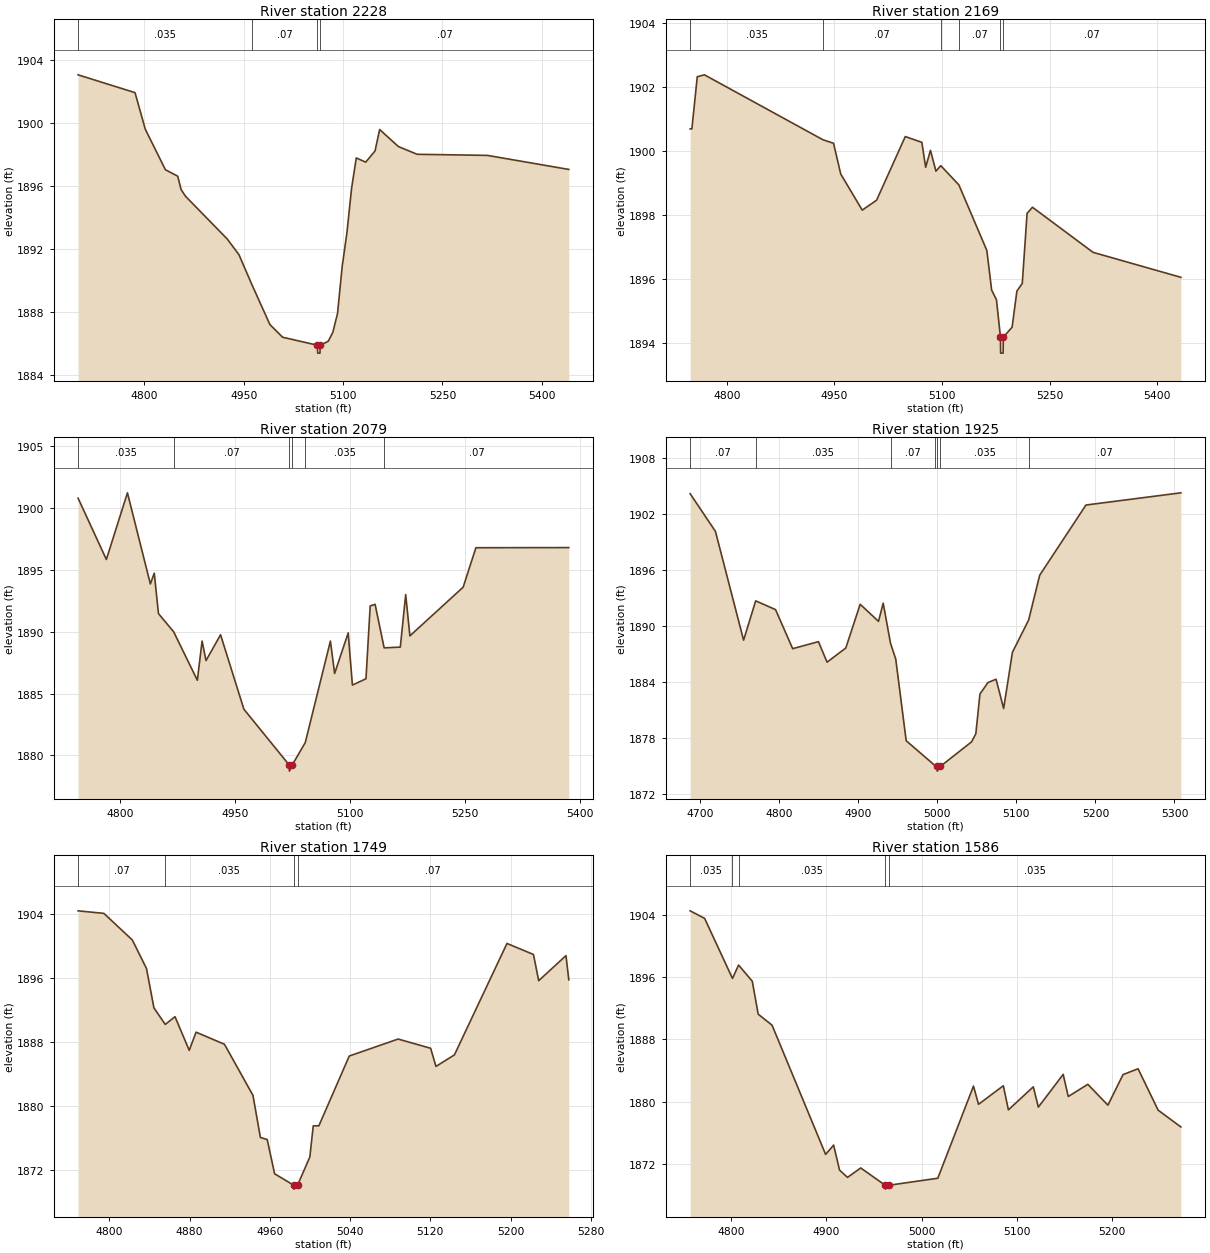
Type RM Length L Ch R = 1 ,2228    ,59,59,59
BEGIN DESCRIPTION:
Elm 01 11 2227.61
END DESCRIPTION:
XS GIS Cut Line= 3
      1568907.49      6799687.56      1568952.63      6799993.14
      1569261.63      6800295.19
#Sta/Elev= 30
  4699.8 1903.06  4785.8 1901.93  4801.3 1899.61  4831.7 1897.04  4850.3 1896.63
  4855.4 1895.78    4862 1895.36    4925 1892.65  4942.8 1891.65  4961.8  1889.8
  4989.5 1887.22  5008.6 1886.42  5061.3 1885.91  5061.6 1885.41  5065.1 1885.41
  5065.3 1885.91  5077.5 1886.16  5084.5 1886.73  5091.6 1887.93  5098.6  1890.9
  5105.8 1893.06  5112.8 1895.86  5119.9 1897.79  5134.1 1897.52  5148.2 1898.23
  5155.2 1899.59  5183.5 1898.51  5211.8 1898.02  5317.9 1897.95  5440.8 1897.06
#Mann= 4 ,-1 , 0
  4699.8    .035       0  4961.8     .07       0  5061.3     .07       0
  5065.3     .07       0
Bank Sta=5061.3,5065.3
XS Rating Curve= 0 ,0
Exp/Cntr=0.3,0.1

Type RM Length L Ch R = 1 ,2169    ,90,90,90
BEGIN DESCRIPTION:
Elm 01 11 1.0
END DESCRIPTION:
XS GIS Cut Line= 3
      1568894.05      6799738.13       1568892.9      6800057.33
      1569134.83       6800330.5
#Sta/Elev= 30
    4749  1900.7  4751.4  1900.7  4758.9 1902.33  4768.9 1902.39  4934.1 1900.36
  4948.9 1900.25  4958.9 1899.29  4988.9 1898.16  5008.9 1898.47  5048.9 1900.46
    5072 1900.28  5077.3  1899.5    5084 1900.03  5091.6 1899.38  5098.4 1899.55
  5123.6 1898.95  5162.6  1896.9  5169.3 1895.66    5176 1895.36  5181.6 1894.19
  5181.8 1893.69  5185.3 1893.69  5185.6 1894.19  5197.8  1894.5  5204.5 1895.63
    5212 1895.87  5218.7 1898.06  5226.2 1898.25  5310.7 1896.84  5433.1 1896.06
#Mann= 6 ,-1 , 0
    4749    .035       0  4934.1     .07       0  5098.4    .035       0
  5123.6     .07       0  5181.6     .07       0  5185.6     .07       0
Bank Sta=5181.6,5185.6
XS Rating Curve= 0 ,0
Exp/Cntr=0.3,0.1

Type RM Length L Ch R = 1 ,2079    ,154,154,154
BEGIN DESCRIPTION:
Elm 01 11 2079.04
END DESCRIPTION:
XS GIS Cut Line= 3
      1568855.42      6799774.35      1568813.74      6800038.28
      1568966.52      6800378.56
#Sta/Elev= 30
  4745.4 1900.81  4782.3 1895.85  4809.8 1901.24  4839.7 1893.87  4844.8 1894.74
  4850.3 1891.47  4870.1    1890    4901 1886.08  4907.2 1889.25  4912.3 1887.67
  4931.3 1889.76  4961.7 1883.74  5020.8 1879.23  5021.1 1878.73  5024.8 1879.23
  5041.8 1881.04  5074.6 1889.25  5080.1 1886.63  5097.8 1889.91  5103.3 1885.69
    5121  1886.2  5126.5 1892.09  5132.9 1892.22  5144.7  1888.7  5165.8 1888.76
  5172.8 1893.01  5178.3 1889.67  5247.8 1893.61  5264.4  1896.8  5385.6 1896.81
#Mann= 6 ,-1 , 0
  4745.4    .035       0  4870.1     .07       0  5020.8     .07       0
  5024.8     .07       0  5041.8    .035       0  5144.7     .07       0
Bank Sta=5020.8,5024.8
XS Rating Curve= 0 ,0
Exp/Cntr=0.3,0.1

Type RM Length L Ch R = 1 ,1925    ,176,176,176
BEGIN DESCRIPTION:
Elm 01 11 1925.23
END DESCRIPTION:
XS GIS Cut Line= 3
      1568855.42      6799628.53      1568730.41       6799923.7
      1568654.34      6800214.15
#Sta/Elev= 30
  4687.3 1904.19  4719.3 1900.14  4754.9 1888.47  4770.2 1892.69  4795.3 1891.75
    4817 1887.56  4849.6 1888.31  4860.5 1886.11  4884.2 1887.63  4902.4 1892.32
  4925.6 1890.49  4931.5 1892.44  4940.8 1888.13  4947.4 1886.44  4960.6 1877.68
  4997.3    1875  4999.7 1874.92  4999.9 1874.42  5003.7 1874.92  5043.3 1877.56
  5048.7 1878.43  5053.9 1882.69    5064 1883.92  5074.3 1884.28  5083.9 1881.14
    5095 1887.17  5115.5 1890.63  5129.5 1895.44    5188 1902.97  5308.1 1904.28
#Mann= 7 ,-1 , 0
  4687.3     .07       0  4770.2    .035       0  4940.8     .07       0
  4997.3    .035       0  4999.7    .035       0  5003.7    .035       0
  5115.5     .07       0
Bank Sta=4999.7,5003.7
XS Rating Curve= 0 ,0
Exp/Cntr=0.3,0.1

Type RM Length L Ch R = 1 ,1749    ,163,163,163
BEGIN DESCRIPTION:
Elm 01 11 1748.75
END DESCRIPTION:
XS GIS Cut Line= 3
      1568765.13      6799621.61      1568605.41      6799795.23
       1568529.5      6800036.77
#Sta/Elev= 30
  4768.9 1904.39  4794.6 1904.07    4823 1900.74  4837.1 1897.17  4844.5 1892.25
  4855.8 1890.18  4865.5 1891.15  4879.7 1886.94  4886.5 1889.21  4914.8  1887.7
  4943.2 1881.31  4950.6 1876.05  4957.4 1875.78  4964.8  1871.5  4983.7 1870.08
    4984 1869.58  4987.7 1870.08  4999.9  1873.6  5003.3  1877.5  5008.9  1877.5
  5039.2 1886.23  5087.9 1888.35  5120.3  1887.2  5125.6 1884.93    5144 1886.37
  5196.4 1900.31  5222.8 1898.93    5228 1895.65  5255.2 1898.79    5258 1895.76
#Mann= 4 ,-1 , 0
  4768.9     .07       0  4855.8    .035       0  4983.7     .07       0
  4987.7     .07       0
Bank Sta=4983.7,4987.7
XS Rating Curve= 0 ,0
Exp/Cntr=0.3,0.1

Type RM Length L Ch R = 1 ,1586    ,120,120,120
BEGIN DESCRIPTION:
Elm 01 11 1586.22
END DESCRIPTION:
XS GIS Cut Line= 3
      1568688.77      6799531.32      1568483.88      6799684.12
      1568400.55      6799930.63
#Sta/Elev= 30
  4756.7 1904.53  4771.9 1903.56  4801.2 1895.84  4807.6 1897.56    4822 1895.48
  4828.2 1891.25  4842.8 1889.83  4899.1 1873.22  4907.5 1874.42  4913.7 1871.21
  4922.1 1870.27    4936 1871.48  4961.7 1869.26    4962 1868.76  4965.7 1869.26
    5017 1870.16  5054.5    1882  5059.8 1879.66  5085.9 1882.05  5091.2 1878.95
  5117.4 1881.91  5122.7  1879.3  5148.8 1883.51  5154.1 1880.66  5174.7 1882.23
  5195.8 1879.55  5211.7 1883.48  5227.5 1884.23  5248.6 1878.91  5272.5 1876.75
#Mann= 5 ,-1 , 0
  4756.7    .035       0  4801.2     .07       0  4807.6    .035       0
  4961.7    .035       0  4965.7    .035       0
Bank Sta=4961.7,4965.7
XS Rating Curve= 0 ,0
Exp/Cntr=0.3,0.1