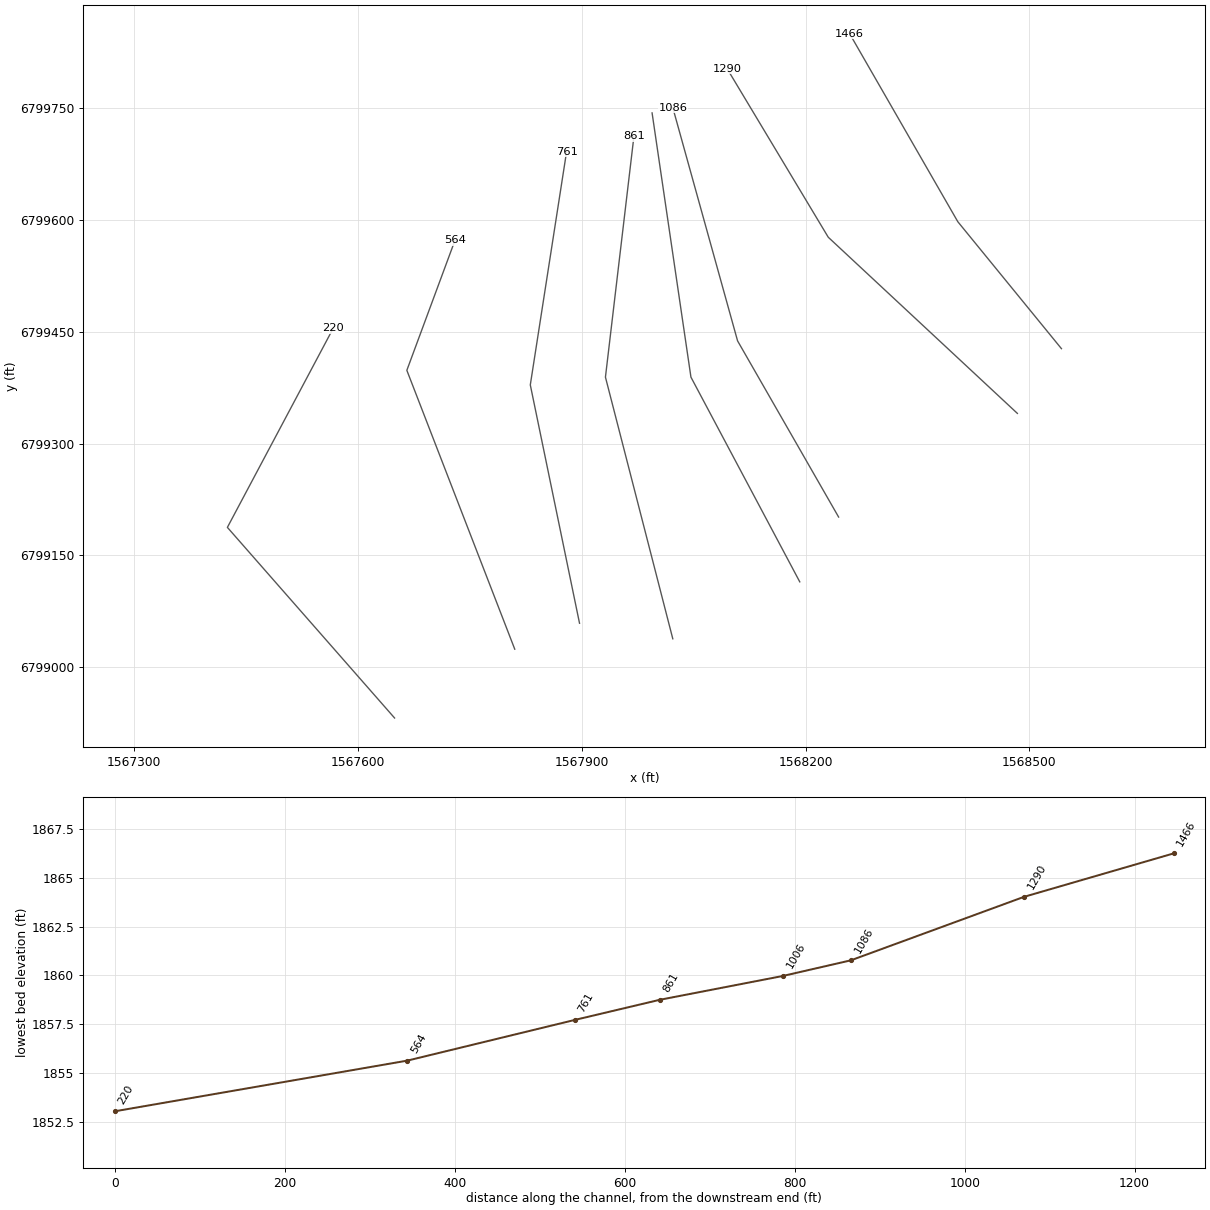
HEC-RAS study Elm 01 11.prj: Elm 01 11 Base Level Engineering

--- Elm 01 11.g01 (geometry) --- (continued)

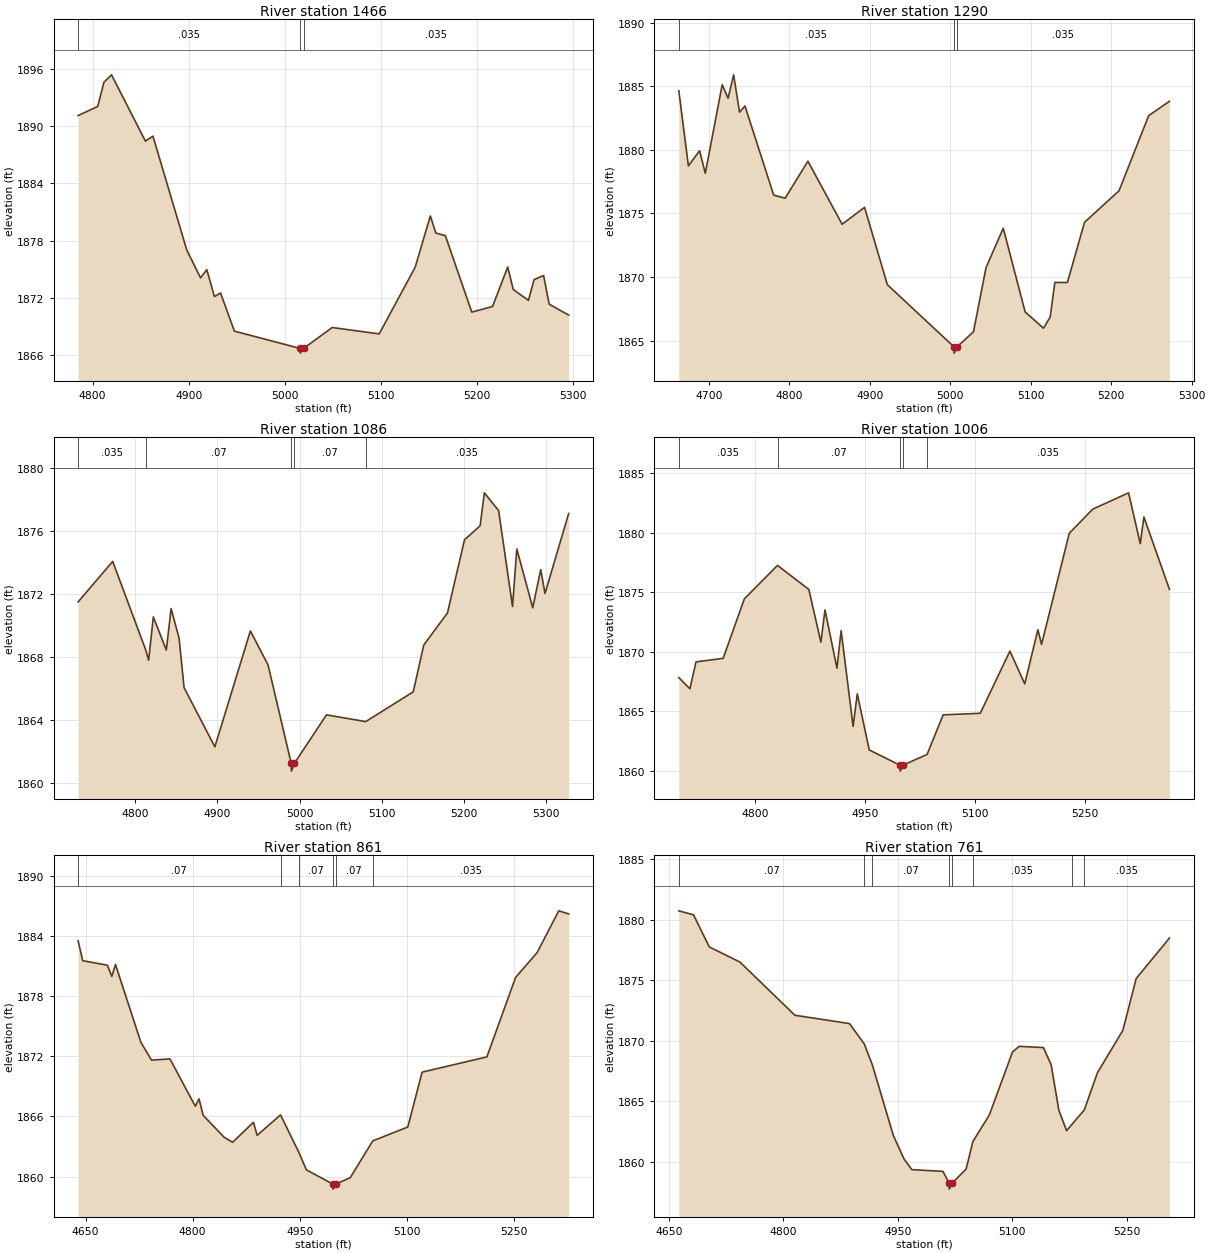
Type RM Length L Ch R = 1 ,1466    ,176,176,176
BEGIN DESCRIPTION:
Elm 01 11 1465.87
END DESCRIPTION:
XS GIS Cut Line= 3
      1568542.92      6799427.15      1568404.02      6799597.31
      1568259.08      6799849.24
#Sta/Elev= 30
  4784.9 1891.09  4805.3 1892.04  4811.8 1894.57  4819.7 1895.35  4854.9 1888.42
  4862.8 1888.93    4898 1877.01  4912.3 1874.11  4918.8 1874.97  4926.7 1872.16
  4933.1 1872.53  4947.5 1868.54  5015.6 1866.74  5015.9 1866.24  5019.6 1866.74
  5049.2 1868.92  5098.1 1868.25  5135.5 1875.22  5151.3 1880.59    5157  1878.8
  5166.9 1878.53  5194.4 1870.53    5216 1871.12  5231.8 1875.25  5237.5  1872.9
  5253.3 1871.76  5259.2 1873.93  5269.1 1874.36  5274.9 1871.36  5295.2 1870.22
#Mann= 3 ,-1 , 0
  4784.9    .035       0  5015.6    .035       0  5019.6    .035       0
Bank Sta=5015.6,5019.6
XS Rating Curve= 0 ,0
Exp/Cntr=0.3,0.1

Type RM Length L Ch R = 1 ,1290    ,204,204,204
BEGIN DESCRIPTION:
Elm 01 11 1289.82
END DESCRIPTION:
XS GIS Cut Line= 3
      1568483.87      6799340.38      1568230.41      6799576.48
      1568094.99      6799802.18
#Sta/Elev= 30
  4662.8 1884.65  4674.7 1878.74  4688.6 1879.93  4695.7 1878.16  4716.7 1885.12
    4724 1884.06  4730.9  1885.9  4738.2 1882.97    4745 1883.45  4780.7 1876.44
  4794.9  1876.2  4823.2 1879.11  4865.7 1874.15  4893.6 1875.48  4921.9  1869.4
  5004.6 1864.52  5004.9 1864.02  5008.6 1864.52  5028.9  1865.7  5044.5 1870.74
  5065.9 1873.84  5093.1 1867.26  5115.9 1865.98  5124.2 1866.85    5130 1869.58
  5145.6 1869.57  5166.9 1874.31  5209.7 1876.78  5246.6 1882.69  5272.4 1883.82
#Mann= 3 ,-1 , 0
  4662.8    .035       0  5004.6    .035       0  5008.6    .035       0
Bank Sta=5004.6,5008.6
XS Rating Curve= 0 ,0
Exp/Cntr=0.3,0.1

Type RM Length L Ch R = 1 ,1086    ,80,80,80
BEGIN DESCRIPTION:
Elm 01 11 1086.35
END DESCRIPTION:
XS GIS Cut Line= 3
       1568244.3      6799201.47      1568108.88      6799437.59
      1568022.08      6799750.06
#Sta/Elev= 30
  4730.7  1871.5  4772.8 1874.07  4813.2 1868.42  4816.5  1867.8  4822.2 1870.55
    4838 1868.45  4843.8 1871.08  4853.5  1869.2  4859.6 1866.06    4897 1862.31
  4940.2 1869.66  4961.7  1867.5  4989.8 1861.27  4990.1 1860.77  4993.8 1861.27
  5032.7 1864.34  5080.4 1863.91  5138.2  1865.8    5151 1868.77  5179.8  1870.8
  5200.5 1875.44  5219.5 1876.33  5224.7 1878.42    5242 1877.29  5258.9 1871.21
  5264.1 1874.86  5283.5 1871.13  5293.2 1873.55  5298.4 1872.04  5327.2 1877.11
#Mann= 5 ,-1 , 0
  4730.7    .035       0  4813.2     .07       0  4989.8     .07       0
  4993.8     .07       0  5080.4    .035       0
Bank Sta=4989.8,4993.8
XS Rating Curve= 0 ,0
Exp/Cntr=0.3,0.1

Type RM Length L Ch R = 1 ,1006    ,145,145,145
BEGIN DESCRIPTION:
Elm 01 11 1005.77
END DESCRIPTION:
XS GIS Cut Line= 3
      1568192.22      6799114.65      1568046.38      6799388.98
      1567994.31      6799743.09
#Sta/Elev= 30
  4696.1 1867.83  4711.2 1866.89  4719.5 1869.15  4756.5 1869.45  4785.4 1874.45
  4830.6 1877.26  4873.3 1875.24  4889.7 1870.81  4895.3 1873.52  4911.6 1868.62
  4917.3 1871.78  4933.6 1863.73  4939.3 1866.46  4955.6 1861.75  4997.5 1860.47
  4997.8 1859.97  5001.5 1860.47  5034.4 1861.37  5056.3  1864.7  5106.9 1864.83
  5147.3 1870.06  5167.5  1867.3  5185.4 1871.86  5190.4 1870.62  5228.2 1879.96
  5260.2 1881.99    5309 1883.36  5324.9 1879.09  5329.9 1881.33  5364.7 1875.25
#Mann= 5 ,-1 , 0
  4696.1    .035       0  4830.6     .07       0  4997.5     .07       0
  5001.5     .07       0  5034.4    .035       0
Bank Sta=4997.5,5001.5
XS Rating Curve= 0 ,0
Exp/Cntr=0.3,0.1

Type RM Length L Ch R = 1 ,861     ,100,100,100
BEGIN DESCRIPTION:
Elm 01 11 860.65
END DESCRIPTION:
XS GIS Cut Line= 3
      1568022.06      6799038.33       1567931.8      6799388.98
      1567969.99      6799711.85
#Sta/Elev= 30
  4639.5 1883.52    4646 1881.52  4680.5 1881.07  4686.8 1879.96  4691.9 1881.14
  4727.5 1873.38  4742.4 1871.61  4768.2 1871.73  4803.7 1867.01  4808.9 1867.75
  4814.7 1866.11  4844.4  1863.9    4856 1863.42  4885.1 1865.41  4890.3 1864.11
  4923.1 1866.15  4948.7 1862.42  4959.3 1860.67  4996.5 1859.25  4996.7 1858.75
  5000.5 1859.25  5020.7 1859.89  5052.3 1863.56  5101.3 1864.94  5121.4 1870.41
  5212.1 1871.93  5252.3 1879.85  5282.5 1882.33  5312.8 1886.49  5326.7 1886.18
#Mann= 6 ,-1 , 0
  4639.5     .07       0  4923.1    .035       0  4948.7     .07       0
  4996.5     .07       0  5000.5     .07       0  5052.3    .035       0
Bank Sta=4996.5,5000.5
XS Rating Curve= 0 ,0
Exp/Cntr=0.3,0.1

Type RM Length L Ch R = 1 ,761     ,197,197,197
BEGIN DESCRIPTION:
Elm 01 11 761.15
END DESCRIPTION:
XS GIS Cut Line= 3
      1567897.07      6799059.16       1567831.1      6799378.56
      1567879.72      6799691.06
#Sta/Elev= 30
  4663.2 1880.72  4682.4 1880.39  4703.1 1877.74  4743.1 1876.49  4815.2 1872.09
  4886.7  1871.4    4906 1869.72  4916.6 1867.99  4944.1 1862.15  4958.1 1860.21
  4968.3 1859.33    5009 1859.19  5017.1 1858.22  5017.4 1857.72  5021.1 1858.22
  5039.4 1859.38  5048.2 1861.65  5069.7 1863.84  5100.1 1869.05  5108.7 1869.52
  5140.6 1869.42  5150.7    1868  5160.8 1864.24  5170.9 1862.55  5177.5 1863.04
  5194.1 1864.26  5211.4 1867.35  5244.6 1870.84    5262 1875.12  5305.6 1878.47
#Mann= 8 ,-1 , 0
  4663.2     .07       0    4906    .035       0  4916.6     .07       0
  5017.1     .07       0  5021.1     .07       0  5048.2    .035       0
  5177.5     .07       0  5194.1    .035       0
Bank Sta=5017.1,5021.1
XS Rating Curve= 0 ,0
Exp/Cntr=0.3,0.1

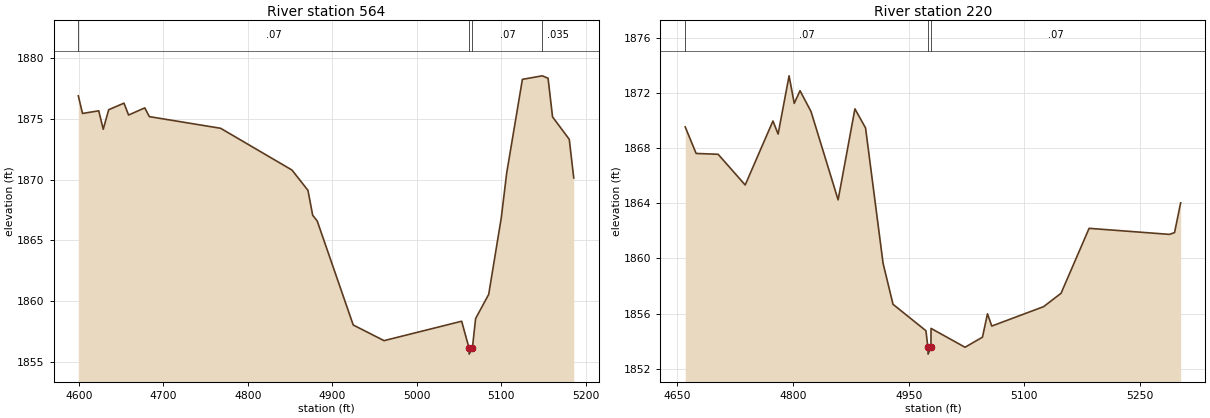
Type RM Length L Ch R = 1 ,564     ,344,344,344
BEGIN DESCRIPTION:
Elm 01 11 563.62
END DESCRIPTION:
XS GIS Cut Line= 3
      1567810.26      6799024.42      1567665.65      6799398.11
       1567730.2      6799572.44
#Sta/Elev= 30
  4599.3 1876.91  4604.3 1875.46  4623.5 1875.68  4628.8 1874.16  4635.3 1875.77
  4653.4 1876.31  4658.8 1875.33    4678 1875.92  4683.4  1875.2  4767.8 1874.24
  4852.3  1870.8  4871.2 1869.13  4876.8 1867.08  4882.2  1866.6  4924.8 1858.04
  4961.3 1856.75  5053.2 1858.35  5061.9 1856.14  5062.1 1855.64  5065.9 1856.14
  5069.7 1858.57  5085.2 1860.56  5100.1 1866.87  5106.5 1870.55  5125.1 1878.27
  5148.6 1878.56  5155.5 1878.36  5160.8 1875.18  5180.6 1873.33  5185.9 1870.15
#Mann= 4 ,-1 , 0
  4599.3     .07       0  5061.9     .07       0  5065.9     .07       0
  5148.6    .035       0
Bank Sta=5061.9,5065.9
XS Rating Curve= 0 ,0
Exp/Cntr=0.3,0.1

Type RM Length L Ch R = 1 ,220     ,0,0,0
BEGIN DESCRIPTION:
Elm 01 11 3747
END DESCRIPTION:
XS GIS Cut Line= 3
      1567649.21      6798932.17      1567425.15      6799187.63
      1567567.21      6799454.93
#Sta/Elev= 30
  4660.2 1869.56  4674.4 1867.63  4702.9 1867.57    4738 1865.34    4774 1869.99
  4780.7 1869.04  4794.9 1873.27  4801.6 1871.27  4809.1 1872.19  4823.4 1870.67
  4858.5 1864.26  4880.3 1870.87  4894.1 1869.48  4916.8 1859.65  4929.7 1856.67
  4972.4 1854.75  4974.9 1853.55  4975.2 1853.05  4978.9 1853.55    4979 1854.92
  5023.1 1853.55  5045.7 1854.28  5052.2 1855.98  5057.8 1855.09    5125  1856.5
  5147.6 1857.47    5184 1862.19  5288.3 1861.75  5294.8 1861.88  5302.7 1864.04
#Mann= 3 ,-1 , 0
  4660.2     .07       0  4974.9     .07       0  4978.9     .07       0
Bank Sta=4974.9,4978.9
XS Rating Curve= 0 ,0
Exp/Cntr=0.3,0.1

Chan Stop Cuts=-1
Use User Specified Reach Order=0
Composite Channel Slope=5