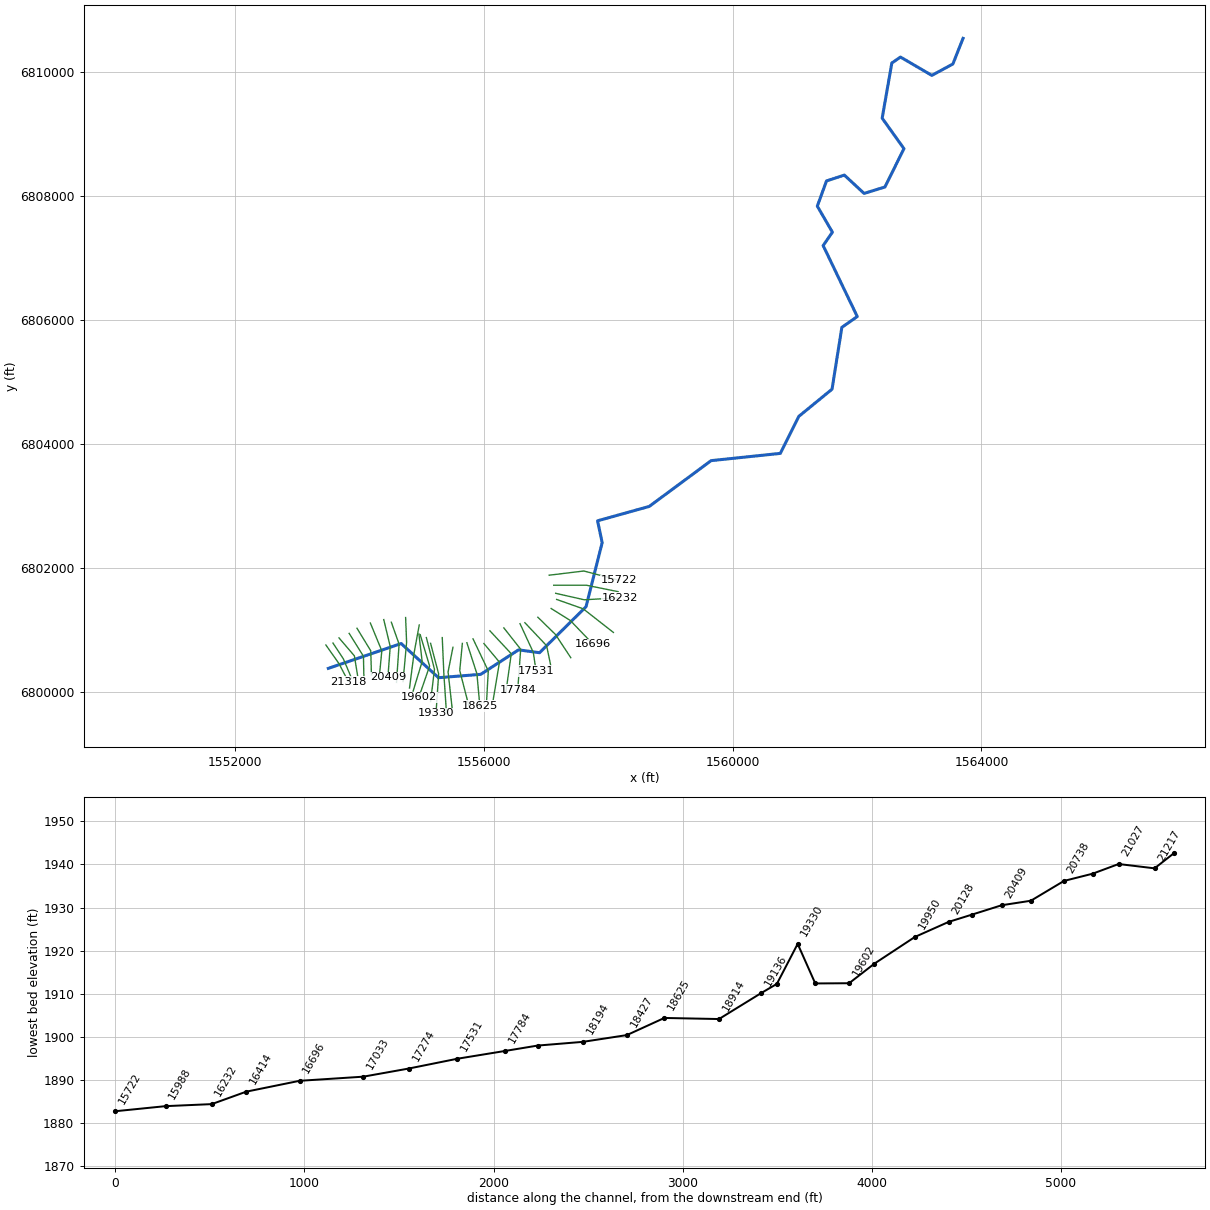
--- Elm 01 12.prj (project) ---

Proj Title=Elm 01 12 Base Level Engineering
Current Plan=p01
Default Exp/Contr=0.3,0.1
English Units
Geom File=g01
Flow File=f01
Plan File=p01
Y Axis Title=Elevation
X Axis Title(PF)=Main Channel Distance
X Axis Title(XS)=Station
BEGIN DESCRIPTION:
Elm 01 12
END DESCRIPTION:
DSS Export Rating Curves= 0
DSS Export Rating Curve Sorted= 0
DSS Export Volume Flow Curves= 0
DXF OffsetX= 0
DXF OffsetY= 0
DXF ScaleX= 1
DXF ScaleY= 10

--- Elm 01 12.p01 (plan) ---

Plan Title=Multiple Run
Program Version=4.10
Short Identifier=Multiple
Geom File=g01
Flow File=f01
Subcritical Flow
K Sum by GR= 0
Std Step Tol= 0.01
Critical Tol= 0.01
Num of Std Step Trials= 20
Max Error Tol= 0.3
Flow Tol Ratio= 0.001
Split Flow NTrial= 30
Split Flow Tol= 0.02
Split Flow Ratio= 0.02
Log Output Level= 0
Friction Slope Method= 1
Unsteady Friction Slope Method= 2
Unsteady Bridges Friction Slope Method= 1
Parabolic Critical Depth
Global Vel Dist= 1 , 1 , 1
Global Log Level= 0
CheckData=True
Encroach Param=-1 ,0,0, 0
BEGIN DESCRIPTION:
Multiple Run
END DESCRIPTION:
Computation Interval=1HOUR
Output Interval=1HOUR
Run HTab= 0
Run UNet= 0
Run PostProcess= 0
Run WQNet= 0
UNET Theta= 1
UNET Theta Warmup= 1
UNET ZTol= 0.02
UNET ZSATol= 0.05
UNET MxIter= 20
UNET MaxInSteps= 0
UNET DtIC= 0
UNET DtMin= 0
UNET MaxCRTS= 20
UNET WFStab= 2
UNET SFStab= 1
UNET WFX= 1
UNET SFX= 1
UNET DSS MLevel= 4
UNET DZMax Abort= 100
UNET Convert EG Bridges= 0
UNET Use Existing IB Tables=-1
UNET Froude Reduction=False
UNET Froude Limit= 1
UNET Froude Power= 10
UNET Time Slicing=0,0, 5
UNET Junction Losses=0
Instantaneous Interval=1HOUR
Write IC File= 0
Write IC File at Sim End=0
Echo Input=False
Echo Parameters=False
Echo Output=False
Write Detailed= 0
WQ AD Non Conservative
WQ ULTIMATE=-1
WQ Max Comp Step=1HOUR
WQ Output Interval=15MIN
WQ Output Selected Increments= 0
WQ Output face flow=0
WQ Output face velocity=0
WQ Output face area=0
WQ Output face dispersion=0
WQ Output cell volume=0
WQ Output cell surface area=0
WQ Output cell continuity=0
WQ Output cumulative cell continuity=0
WQ Output face conc=0
WQ Output face dconc_dx=0
WQ Output face courant=0
WQ Output face peclet=0
WQ Output face adv mass=0
WQ Output face disp mass=0
WQ Output cell mass=0
WQ Output cell source sink temp=0
WQ Output cell source sink nsm=0
WQ Output MaxMinRange=-1
WQ Daily Max Min Mean=-1
WQ Daily Range=0
WQ Daily Time=0
WQ Create Restart=0
WQ Fixed Restart=0
WQ System Summary=0
WQ Use Fixed Temperature=0
Sorting and Armoring Iterations= 10
XS Update Threshold= 0.02
Hydraulics Update Threshold= 0.02
Energy Slope Method= 1
Volume Change Method= 0
XS Weighting Method= 0
Number of US Weighted Cross Sections= 1
Number of DS Weighted Cross Sections= 1
Upstream XS Weight=0.25
Main XS Weight=0.5
Downstream XS Weight=0.25
Number of DS XS's Weighted with US Boundary= 1
Upstream Boundary Weight= 1
Weight of XSs Associated with US Boundary= 0
Number of US XS's Weighted with DS Boundary= 1
Downstream Boundary Weight= 0.5
Weight of XSs Associated with DS Boundary= 0.5
Sediment Output Level= 4
Mass or Volume Output= 0
Output Increment Type= 1
Profile and TS Output Increment= 10
XS Output Flag= 0
XS Output Increment= 10
Disregard all LS=0
Disregard all Conn=0
Disregard all Breaches=0
Disregard all Pumps=0

--- Elm 01 12.f01 (steady flow) ---

Flow Title=Multiple
Number of Profiles=7
Profile Names=10-year,25-year,50-year,1pct_min,100-year,1pct_plu,500-year
River Rch & RM= Elm 01 12,Reach-1,21318
     209     288     353     269     432     594     652
River Rch & RM= Elm 01 12,Reach-1,10879
     276     387     479     368     590     812     907
River Rch & RM= Elm 01 12,Reach-1,9058
     427     607     759     587     941    1290    1470
Boundary for River Rch & Prof#=Elm 01 12,Reach-1,1
Up Type=0
Dn Type=3
Dn Slope=0.005
Boundary for River Rch & Prof#=Elm 01 12,Reach-1,2
Up Type=0
Dn Type=3
Dn Slope=0.005
Boundary for River Rch & Prof#=Elm 01 12,Reach-1,3
Up Type=0
Dn Type=3
Dn Slope=0.005
Boundary for River Rch & Prof#=Elm 01 12,Reach-1,4
Up Type=0
Dn Type=3
Dn Slope=0.005
Boundary for River Rch & Prof#=Elm 01 12,Reach-1,5
Up Type=0
Dn Type=3
Dn Slope=0.005
Boundary for River Rch & Prof#=Elm 01 12,Reach-1,6
Up Type=0
Dn Type=3
Dn Slope=0.005
Boundary for River Rch & Prof#=Elm 01 12,Reach-1,7
Up Type=0
Dn Type=3
Dn Slope=0.005

--- Elm 01 12.g01 (geometry) ---

Geom Title=Existing Conditions

River Reach=Elm 01 12,Reach-1
Reach XY= 30
      1553505.00      6800388.00      1554675.10      6800788.10
      1555275.16      6800237.53      1555953.44      6800291.74
      1556561.12      6800686.24      1556899.14      6800640.07
      1557645.87      6801381.26      1557905.59      6802413.17
      1557831.48      6802765.13      1558662.07      6802996.99
      1559656.26      6803734.52      1560768.57      6803851.47
      1561065.77      6804447.70      1561599.55      6804885.53
      1561757.33      6805882.03      1562005.08      6806055.74
      1561456.61      6807199.84      1561605.36      6807414.99
      1561362.79      6807834.58      1561510.52      6808240.44
      1561797.32      6808334.91      1562114.66      6808039.35
      1562449.56      6808143.25      1562755.29      6808760.76
      1562405.10      6809252.04      1562560.46      6810140.47
      1562699.36      6810236.31      1563203.32      6809941.10
      1563541.59      6810124.67      1563705.00      6810538.00

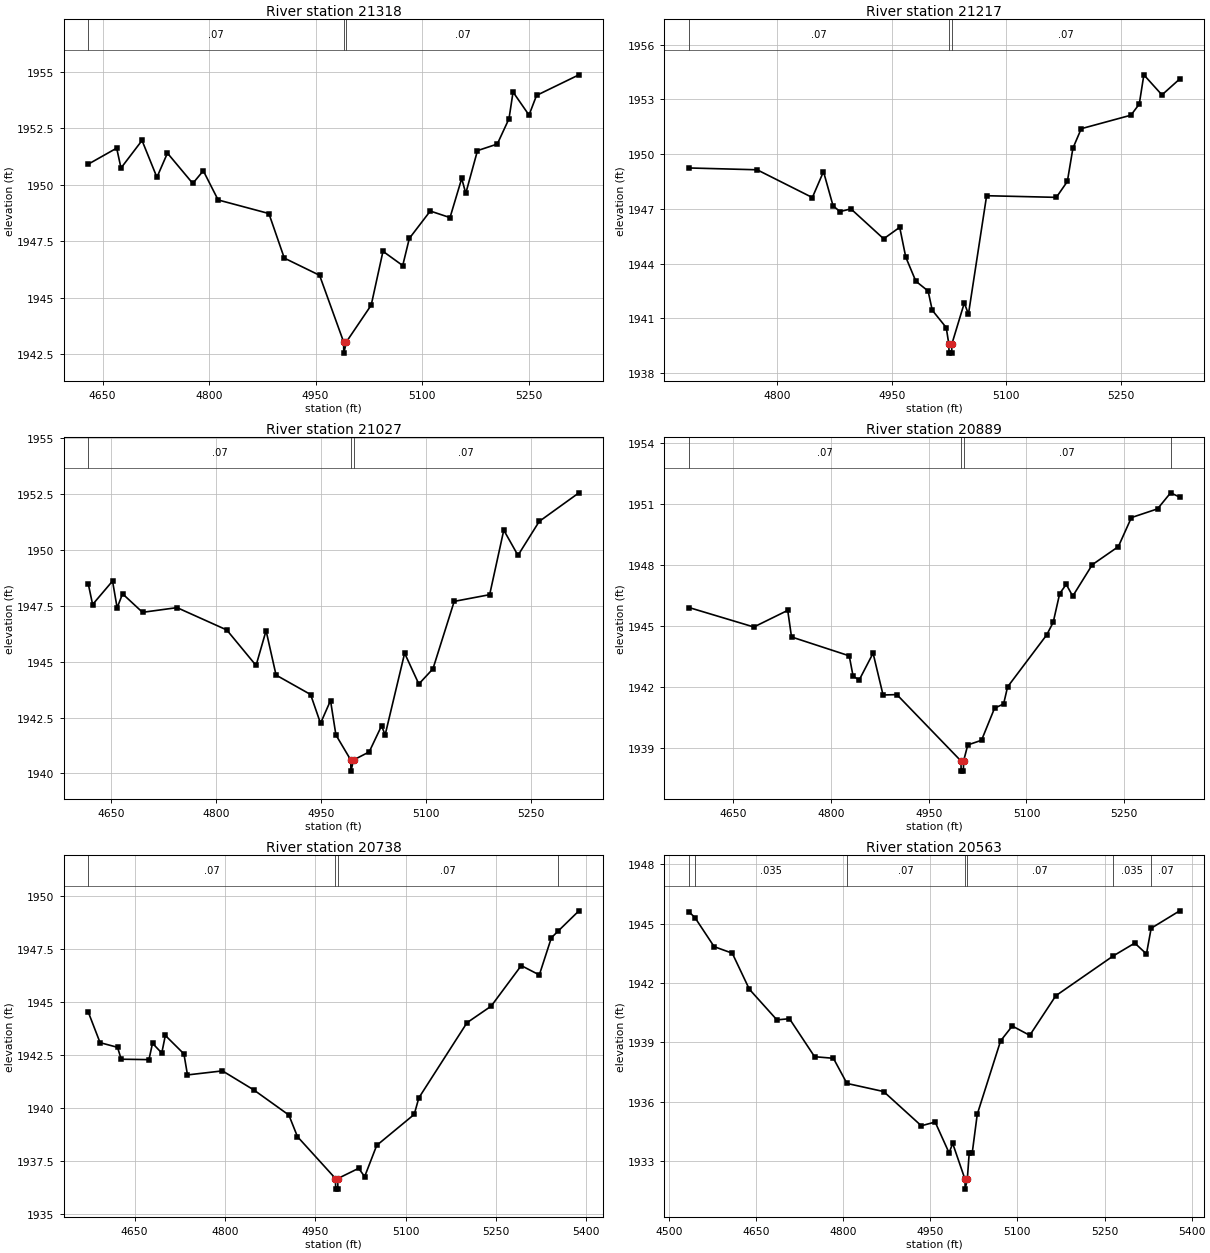
Type RM Length L Ch R = 1,21318,101,101,101
BEGIN DESCRIPTION:
Elm 01 12 21053.495
END DESCRIPTION:
XS GIS Cut Line= 3
      1553465.65      6800763.99      1553678.45      6800461.06
      1553825.01      6800175.47
#Sta/Elev= 30
  4629.8 1950.91  4669.9 1951.62  4676.0 1950.74  4705.6 1951.96  4726.6 1950.33
  4741.4 1951.40  4777.1 1950.06  4791.9 1950.62  4812.8 1949.33  4884.3 1948.73
  4906.0 1946.76  4955.7 1946.00  4989.5 1943.06  4989.8 1942.56  4993.5 1943.06
  5028.4 1944.68  5045.0 1947.06  5072.8 1946.43  5082.1 1947.63  5111.6 1948.84
  5139.4 1948.55  5155.9 1950.28  5161.6 1949.62  5178.1 1951.51  5206.0 1951.80
  5222.5 1952.92  5228.2 1954.10  5250.7 1953.08  5261.3 1953.95  5321.0 1954.86
#Mann=3,-1,0
  4629.8    0.07       0  4989.5    0.07       0  4993.5    0.07       0
Bank Sta=4989.5,4993.5
Exp/Cntr=0.3,0.1

Type RM Length L Ch R = 1,21217,190,190,190
BEGIN DESCRIPTION:
Elm 01 12 21217.33
END DESCRIPTION:
XS GIS Cut Line= 3
      1553579.37      6800795.23      1553746.03      6800541.76
      1553877.99      6800229.23
#Sta/Elev= 30
  4684.3 1949.24  4773.6 1949.14  4845.9 1947.62  4860.5 1949.04  4873.0 1947.17
  4882.1 1946.85  4896.4 1947.00  4939.3 1945.36  4960.3 1945.99  4968.2 1944.36
  4981.4 1943.04  4997.5 1942.50  5002.9 1941.45  5021.2 1940.50  5024.6 1939.60
  5024.9 1939.10  5028.4 1939.10  5028.6 1939.60  5044.9 1941.85  5050.3 1941.23
  5074.1 1947.72  5165.4 1947.63  5179.8 1948.50  5187.1 1950.32  5198.0 1951.39
  5263.1 1952.13  5274.0 1952.74  5280.0 1954.34  5303.7 1953.24  5326.9 1954.11
#Mann=3,-1,0
  4684.3    0.07       0  5024.6    0.07       0  5028.6    0.07       0
Bank Sta=5024.6,5028.6
Exp/Cntr=0.3,0.1

Type RM Length L Ch R = 1,21027,138,138,138
BEGIN DESCRIPTION:
Elm 01 12 21027.39
END DESCRIPTION:
XS GIS Cut Line= 3
      1553676.58      6800878.58      1553923.12      6800590.37
      1553975.03      6800271.94
#Sta/Elev= 30
  4617.3 1948.50  4623.6 1947.56  4652.1 1948.61  4658.7 1947.41  4666.4 1948.04
  4695.0 1947.21  4744.4 1947.42  4815.5 1946.42  4857.4 1944.83  4871.7 1946.39
  4886.0 1944.40  4935.4 1943.53  4949.6 1942.24  4963.9 1943.26  4971.6 1941.72
  4992.8 1940.60  4993.1 1940.10  4996.8 1940.60  5019.2 1940.96  5036.9 1942.13
  5042.0 1941.72  5069.9 1945.38  5090.2 1944.00  5110.4 1944.68  5140.8 1947.70
  5191.5 1948.00  5211.7 1950.89  5232.0 1949.76  5262.4 1951.28  5319.2 1952.56
#Mann=3,-1,0
  4617.3    0.07       0  4992.8    0.07       0  4996.8    0.07       0
Bank Sta=4992.8,4996.8
Exp/Cntr=0.3,0.1

Type RM Length L Ch R = 1,20889,151,151,151
BEGIN DESCRIPTION:
Elm 01 12 20888.65
END DESCRIPTION:
XS GIS Cut Line= 3
      1553839.79      6800951.48      1554068.95      6800583.42
      1554075.90      6800263.96
#Sta/Elev= 30
  4582.0 1945.91  4681.6 1944.95  4733.6 1945.77  4739.4 1944.46  4828.0 1943.53
  4833.9 1942.53  4843.3 1942.34  4864.6 1943.66  4879.9 1941.60  4901.1 1941.62
  4999.5 1938.35  4999.7 1937.85  5003.2 1937.85  5003.5 1938.35  5009.9 1939.14
  5031.0 1939.37  5051.0 1940.95  5064.9 1941.16  5071.0 1942.00  5131.0 1944.56
  5141.0 1945.18  5151.0 1946.60  5161.0 1947.05  5171.0 1946.47  5201.0 1948.02
  5241.0 1948.91  5261.0 1950.34  5301.1 1950.77  5321.2 1951.56  5335.1 1951.35
#Mann=4,-1,0
  4582.0    0.07       0  4999.5    0.07       0  5003.5    0.07       0
  5321.2   0.035       0
Bank Sta=4999.5,5003.5
Exp/Cntr=0.3,0.1

Type RM Length L Ch R = 1,20738,175,175,175
BEGIN DESCRIPTION:
Elm 01 12 20738.4
END DESCRIPTION:
XS GIS Cut Line= 3
      1553964.80      6801034.78      1554187.01      6800670.23
      1554197.40      6800282.20
#Sta/Elev= 30
  4572.9 1944.53  4592.6 1943.08  4621.6 1942.86  4627.7 1942.30  4673.8 1942.28
  4679.7 1943.05  4695.1 1942.59  4701.0 1943.42  4731.9 1942.55  4737.8 1941.56
  4795.9 1941.75  4848.1 1940.85  4906.2 1939.67  4920.5 1938.65  4983.6 1936.68
  4983.9 1936.18  4987.4 1936.18  4987.6 1936.68  5022.1 1937.16  5032.1 1936.77
  5052.1 1938.24  5114.4 1939.70  5122.1 1940.48  5202.1 1944.02  5242.2 1944.80
  5292.2 1946.71  5322.2 1946.27  5342.2 1948.02  5353.6 1948.34  5388.0 1949.29
#Mann=4,-1,0
  4572.9    0.07       0  4983.6    0.07       0  4987.6    0.07       0
  5353.6   0.035       0
Bank Sta=4983.6,4987.6
Exp/Cntr=0.3,0.1

Type RM Length L Ch R = 1,20563,154,154,154
BEGIN DESCRIPTION:
Elm 01 12 20563.45
END DESCRIPTION:
XS GIS Cut Line= 3
      1554180.07      6801118.13      1554364.09      6800670.23
      1554329.55      6800311.02
#Sta/Elev= 30
  4534.3 1945.60  4544.6 1945.31  4577.7 1943.84  4608.9 1943.51  4638.3 1941.69
  4685.8 1940.14  4707.4 1940.20  4750.7 1938.28  4783.1 1938.20  4806.4 1936.93
  4869.6 1936.52  4934.5 1934.79  4958.3 1934.98  4982.3 1933.42  4988.5 1933.90
  5009.7 1932.09  5009.9 1931.59  5013.7 1932.09  5017.0 1933.43  5022.2 1933.43
  5030.8 1935.37  5071.0 1939.08  5091.1 1939.83  5121.2 1939.36  5166.1 1941.36
  5264.9 1943.37  5302.1 1944.02  5322.2 1943.47  5330.3 1944.77  5379.4 1945.65
#Mann=7,-1,0
  4534.3    0.07       0  4544.6   0.035       0  4806.4    0.07       0
  5009.7    0.07       0  5013.7    0.07       0  5264.9   0.035       0
  5330.3    0.07       0
Bank Sta=5009.7,5013.7
Exp/Cntr=0.3,0.1

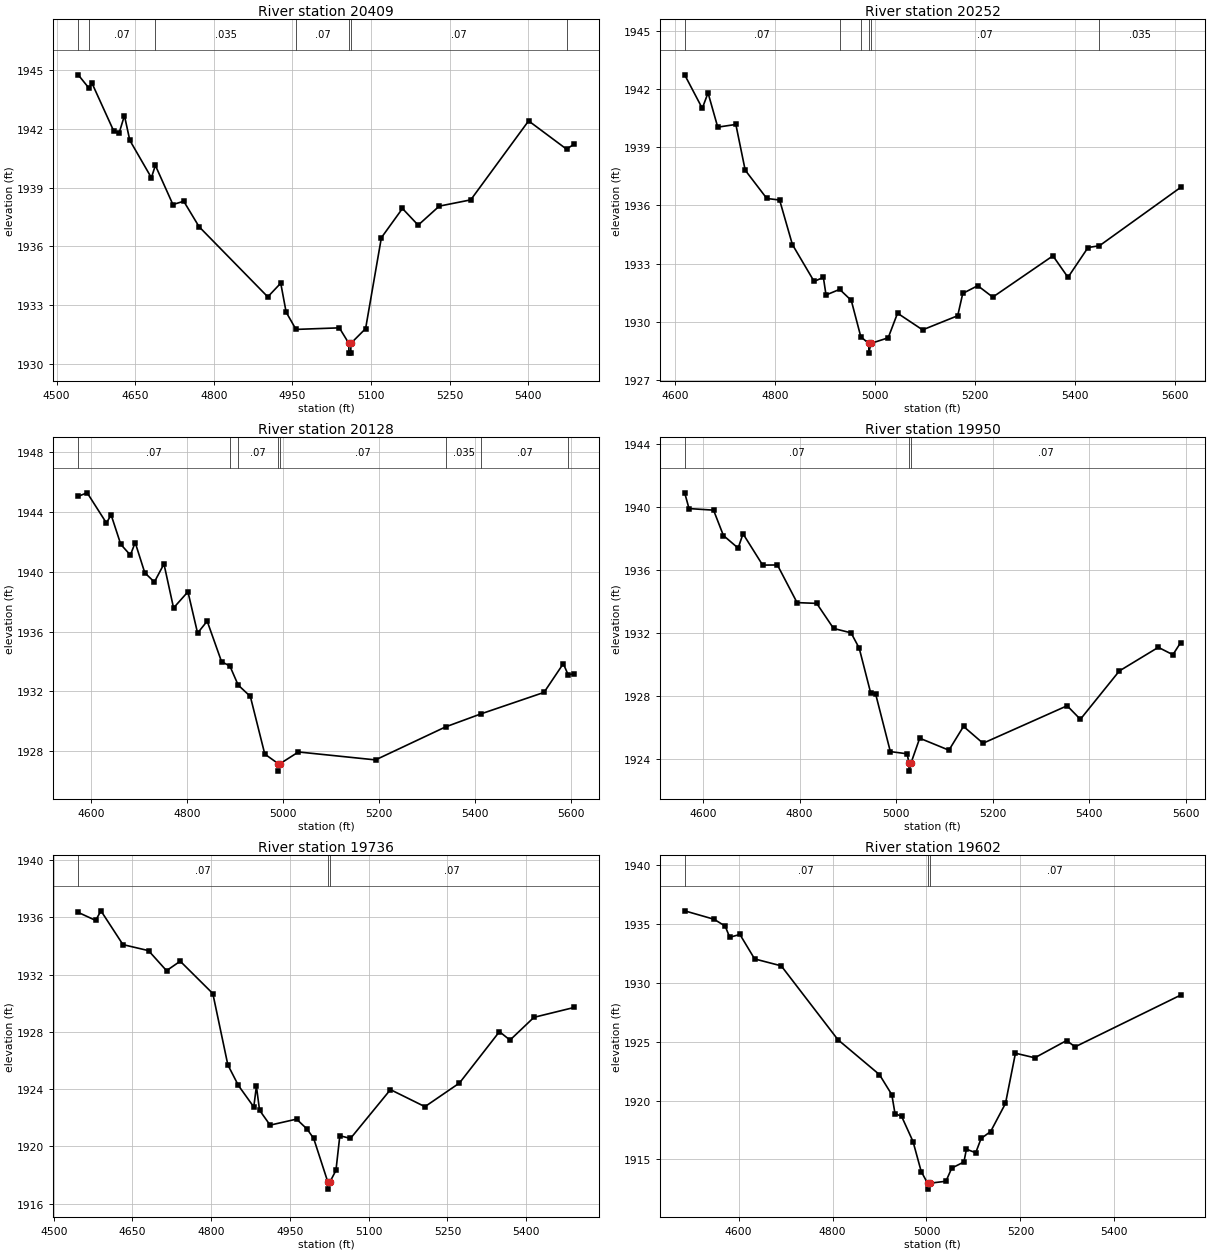
Type RM Length L Ch R = 1,20409,157,157,157
BEGIN DESCRIPTION:
Elm 01 12 20409.16
END DESCRIPTION:
XS GIS Cut Line= 3
      1554395.33      6801173.73      1554499.51      6800739.67
      1554461.44      6800241.30
#Sta/Elev= 30
  4541.3 1944.75  4561.5 1944.08  4567.8 1944.31  4609.1 1941.88  4619.2 1941.77
  4629.5 1942.67  4639.7 1941.41  4680.9 1939.50  4688.5 1940.13  4722.0 1938.13
  4742.6 1938.30  4771.9 1937.00  4903.0 1933.42  4927.7 1934.12  4938.0 1932.64
  4956.8 1931.76  5039.5 1931.84  5057.6 1931.05  5057.8 1930.55  5061.3 1930.55
  5061.6 1931.05  5089.6 1931.80  5119.7 1936.44  5159.9 1937.93  5189.9 1937.08
  5230.1 1938.05  5290.2 1938.37  5400.6 1942.40  5472.9 1940.96  5487.5 1941.21
#Mann=7,-1,0
  4541.3   0.035       0  4561.5    0.07       0  4688.5   0.035       0
  4956.8    0.07       0  5057.6    0.07       0  5061.6    0.07       0
  5472.9   0.035       0
Bank Sta=5057.6,5061.6
Exp/Cntr=0.3,0.1

Type RM Length L Ch R = 1,20252,124,124,124
BEGIN DESCRIPTION:
Elm 01 12 20252.29
END DESCRIPTION:
XS GIS Cut Line= 3
      1554516.85      6801132.07      1554641.87      6800777.87
      1554600.20      6800163.30
#Sta/Elev= 30
  4619.0 1942.74  4654.2 1941.01  4665.7 1941.81  4685.1 1940.04  4721.3 1940.18
  4740.0 1937.82  4783.2 1936.36  4808.8 1936.28  4834.4 1933.98  4877.8 1932.08
  4896.3 1932.29  4901.6 1931.38  4928.9 1931.67  4952.1 1931.10  4971.2 1929.22
  4987.1 1928.88  4987.3 1928.38  4991.1 1928.88  5025.9 1929.17  5044.6 1930.44
  5094.7 1929.58  5164.9 1930.31  5175.0 1931.46  5205.0 1931.86  5235.0 1931.27
  5355.3 1933.40  5385.4 1932.29  5425.5 1933.83  5448.3 1933.92  5610.6 1936.93
#Mann=6,-1,0
  4619.0    0.07       0  4928.9   0.035       0  4971.2    0.07       0
  4987.1    0.07       0  4991.1    0.07       0  5448.3   0.035       0
Bank Sta=4987.1,4991.1
Exp/Cntr=0.3,0.1

Type RM Length L Ch R = 1,20128,178,178,178
BEGIN DESCRIPTION:
Elm 01 12 20127.58
END DESCRIPTION:
XS GIS Cut Line= 3
      1554746.90      6801206.67      1554762.53      6800805.64
      1554705.24      6800175.48
#Sta/Elev= 30
  4573.3 1945.04  4592.0 1945.27  4632.0 1943.26  4642.0 1943.79  4662.0 1941.83
  4682.1 1941.11  4692.1 1941.95  4712.1 1939.93  4732.1 1939.31  4752.1 1940.52
  4772.1 1937.58  4802.1 1938.66  4822.2 1935.90  4842.2 1936.70  4872.2 1933.99
  4889.6 1933.70  4906.8 1932.43  4932.2 1931.67  4962.3 1927.82  4990.3 1927.18
  4990.6 1926.68  4994.3 1927.18  5032.5 1927.96  5193.2 1927.43  5339.7 1929.64
  5413.6 1930.51  5544.6 1931.94  5584.8 1933.86  5594.8 1933.12  5607.4 1933.18
#Mann=8,-1,0
  4573.3    0.07       0  4889.6   0.035       0  4906.8    0.07       0
  4990.3    0.07       0  4994.3    0.07       0  5339.7   0.035       0
  5413.6    0.07       0  5594.8   0.035       0
Bank Sta=4990.3,4994.3
Exp/Cntr=0.3,0.1

Type RM Length L Ch R = 1,19950,214,214,214
BEGIN DESCRIPTION:
Elm 01 12 19950.3
END DESCRIPTION:
XS GIS Cut Line= 3
      1554965.64      6801086.85      1554882.32      6800633.77
      1554809.52      6800072.15
#Sta/Elev= 30
  4562.0 1940.87  4571.0 1939.87  4621.8 1939.77  4642.2 1938.16  4672.7 1937.36
  4682.8 1938.27  4723.5 1936.28  4754.0 1936.29  4794.7 1933.90  4835.4 1933.85
  4870.3 1932.26  4906.5 1931.98  4923.4 1931.01  4947.2 1928.16  4957.4 1928.10
  4987.9 1924.44  5022.7 1924.30  5026.5 1923.70  5026.7 1923.20  5030.5 1923.70
  5048.7 1925.29  5109.2 1924.53  5139.4 1926.04  5179.8 1924.97  5354.0 1927.35
  5381.4 1926.49  5462.1 1929.56  5542.8 1931.06  5573.0 1930.59  5589.0 1931.36
#Mann=3,-1,0
  4562.0    0.07       0  5026.5    0.07       0  5030.5    0.07       0
Bank Sta=5026.5,5030.5
Exp/Cntr=0.3,0.1

Type RM Length L Ch R = 1,19736,134,134,134
BEGIN DESCRIPTION:
Elm 01 12 19735.65
END DESCRIPTION:
XS GIS Cut Line= 3
      1554960.45      6800941.01      1555012.53      6800498.35
      1554867.27      6800021.08
#Sta/Elev= 30
  4546.7 1936.35  4579.9 1935.79  4590.0 1936.46  4631.9 1934.10  4680.6 1933.68
  4714.9 1932.28  4741.0 1932.94  4803.1 1930.68  4831.7 1925.70  4851.8 1924.26
  4881.1 1922.76  4886.1 1924.20  4892.1 1922.53  4912.2 1921.49  4962.6 1921.91
  4982.7 1921.21  4995.2 1920.56  5022.1 1917.52  5022.4 1917.02  5026.1 1917.52
  5037.6 1918.33  5045.0 1920.75  5065.3 1920.56  5141.4 1923.97  5207.1 1922.78
  5272.8 1924.43  5349.0 1928.02  5369.1 1927.43  5414.7 1929.02  5491.3 1929.71
#Mann=3,-1,0
  4546.7    0.07       0  5022.1    0.07       0  5026.1    0.07       0
Bank Sta=5022.1,5026.1
Exp/Cntr=0.3,0.1

Type RM Length L Ch R = 1,19602,179,179,179
BEGIN DESCRIPTION:
Elm 01 12 19602.02
END DESCRIPTION:
XS GIS Cut Line= 3
      1554981.28      6800930.62      1555132.32      6800425.44
      1554960.44      6799925.44
#Sta/Elev= 30
  4485.2 1936.14  4547.9 1935.42  4571.4 1934.84  4581.1 1933.89  4602.8 1934.13
  4634.1 1932.05  4690.8 1931.46  4811.5 1925.18  4899.9 1922.21  4926.3 1920.50
  4933.0 1918.90  4947.2 1918.65  4971.4 1916.52  4988.9 1913.96  5002.5 1912.97
  5002.7 1912.47  5006.5 1912.97  5041.5 1913.14  5053.9 1914.26  5079.8 1914.78
  5085.1 1915.87  5104.9 1915.56  5116.4 1916.78  5136.7 1917.37  5168.3 1919.76
  5189.5 1924.03  5230.7 1923.64  5298.5 1925.11  5316.4 1924.57  5541.2 1928.97
#Mann=3,-1,0
  4485.2    0.07       0  5002.5    0.07       0  5006.5    0.07       0
Bank Sta=5002.5,5006.5
Exp/Cntr=0.3,0.1

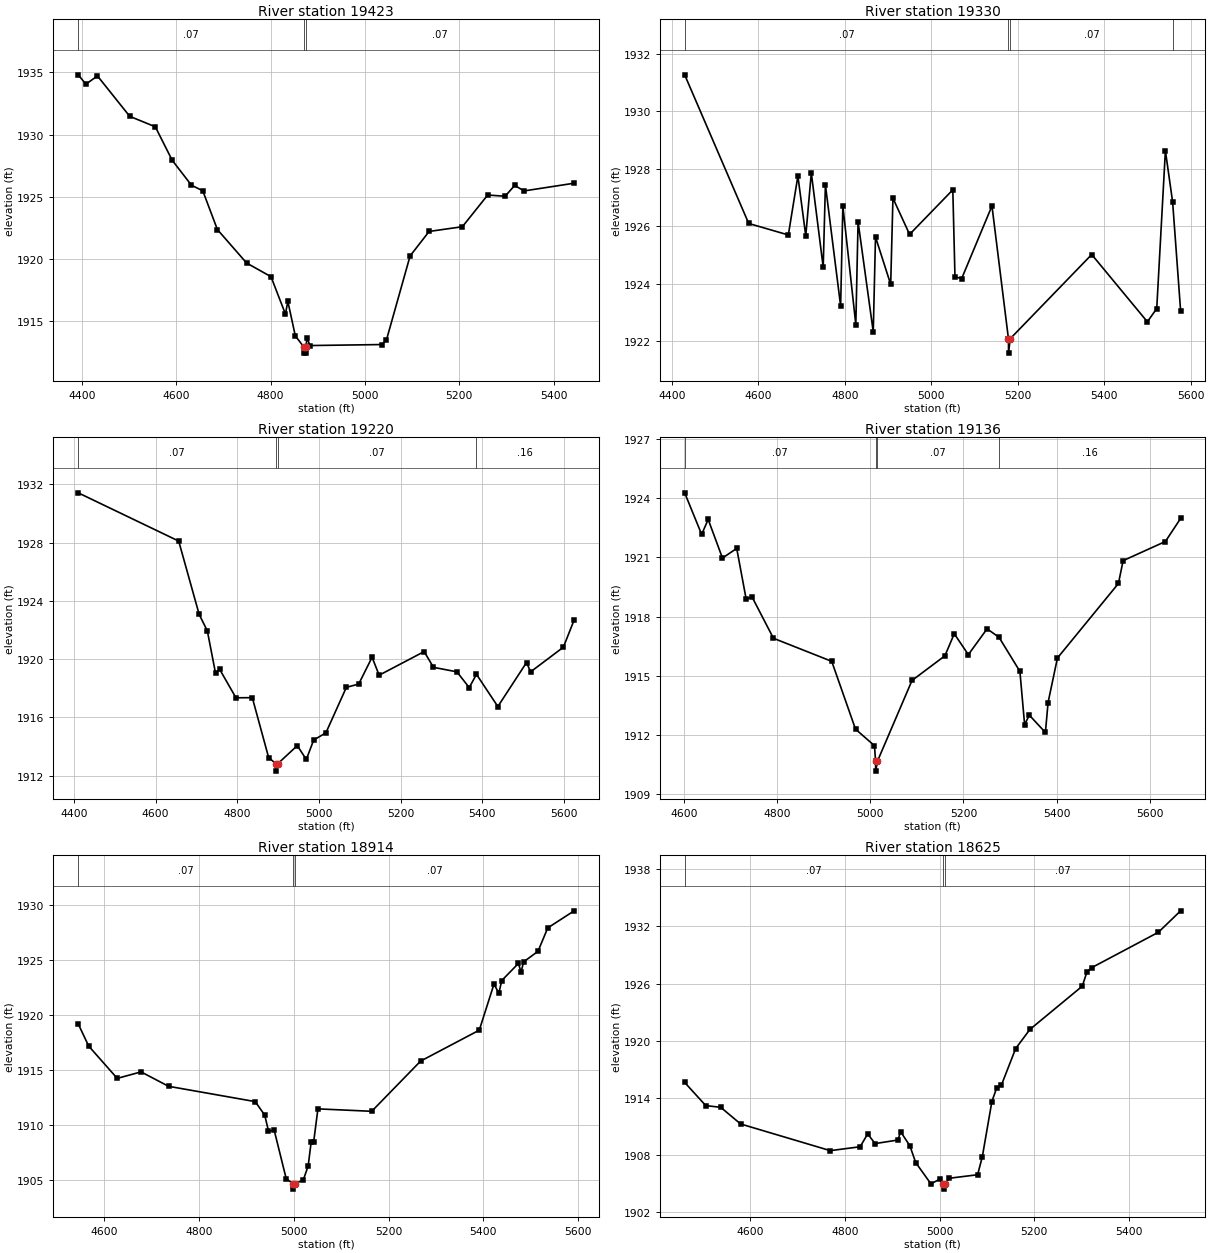
Type RM Length L Ch R = 1,19423,93,93,93
BEGIN DESCRIPTION:
Elm 01 12 19423.44
END DESCRIPTION:
XS GIS Cut Line= 3
      1555080.23      6800883.80      1555210.44      6800373.35
      1555147.98      6799852.78
#Sta/Elev= 30
  4392.3 1934.81  4408.6 1934.06  4433.1 1934.72  4501.5 1931.47  4555.7 1930.63
  4591.4 1927.94  4632.3 1925.93  4656.3 1925.48  4687.3 1922.36  4749.2 1919.67
  4800.9 1918.57  4831.5 1915.56  4836.6 1916.59  4852.4 1913.81  4870.4 1912.92
  4870.6 1912.42  4874.1 1912.42  4874.4 1912.92  4877.5 1913.64  4883.3 1913.03
  5035.3 1913.11  5045.3 1913.44  5095.7 1920.24  5136.0 1922.21  5206.5 1922.59
  5260.2 1925.14  5297.1 1925.04  5317.3 1925.91  5337.4 1925.47  5443.4 1926.09
#Mann=3,-1,0
  4392.3    0.07       0  4870.4    0.07       0  4874.4    0.07       0
Bank Sta=4870.4,4874.4
Exp/Cntr=0.3,0.1

Type RM Length L Ch R = 1,19330,110,110,110
BEGIN DESCRIPTION:
Elm 01 12 2.0
END DESCRIPTION:
XS GIS Cut Line= 3
      1555148.00      6800791.07      1555277.72      6800298.89
      1555235.08      6799662.91
#Sta/Elev= 30
  4429.8 1931.27  4577.8 1926.10  4669.4 1925.70  4691.5 1927.75  4709.7 1925.67
  4722.5 1927.86  4750.0 1924.58  4755.1 1927.44  4790.3 1923.23  4795.4 1926.71
  4825.4 1922.58  4830.6 1926.16  4865.7 1922.33  4870.9 1925.63  4906.0 1923.98
  4911.2 1926.98  4949.7 1925.72  5049.6 1927.27  5054.6 1924.25  5070.0 1924.18
  5140.1 1926.71  5178.2 1922.09  5178.5 1921.59  5182.2 1922.09  5370.7 1925.02
  5499.3 1922.68  5521.0 1923.14  5541.0 1928.63  5557.7 1926.85  5576.2 1923.06
#Mann=4,-1,0
  4429.8    0.07       0  5178.2    0.07       0  5182.2    0.07       0
  5557.7    0.16       0
Bank Sta=5178.2,5182.2
Exp/Cntr=0.3,0.1

Type RM Length L Ch R = 1,19220,84,84,84
BEGIN DESCRIPTION:
Elm 01 12 19220
END DESCRIPTION:
XS GIS Cut Line= 3
      1555335.44      6800883.79      1555361.49      6800295.23
      1555403.06      6799671.65
#Sta/Elev= 30
  4410.7 1931.41  4656.7 1928.10  4706.8 1923.07  4726.8 1921.94  4746.8 1919.05
  4756.8 1919.31  4796.9 1917.35  4836.9 1917.36  4876.9 1913.25  4895.0 1912.82
  4895.2 1912.32  4899.0 1912.82  4947.0 1914.07  4969.1 1913.12  4987.1 1914.45
  5017.1 1914.95  5067.2 1918.07  5097.3 1918.29  5130.1 1920.13  5147.4 1918.90
  5257.6 1920.52  5280.4 1919.44  5337.8 1919.13  5367.9 1918.05  5385.7 1918.96
  5438.0 1916.75  5508.2 1919.77  5518.2 1919.13  5598.4 1920.82  5624.8 1922.69
#Mann=4,-1,0
  4410.7    0.07       0  4895.0    0.07       0  4899.0    0.07       0
  5385.7    0.16       0
Bank Sta=4895,4899
Exp/Cntr=0.3,0.1

Type RM Length L Ch R = 1,19136,222,222,222
BEGIN DESCRIPTION:
Elm 01 12 19135.59
END DESCRIPTION:
XS GIS Cut Line= 3
      1555507.31      6800727.48      1555429.19      6800331.69
      1555502.11      6799675.45
#Sta/Elev= 30
  4602.0 1924.28  4638.4 1922.17  4652.4 1922.93  4683.0 1920.97  4713.6 1921.46
  4734.0 1918.87  4746.2 1919.01  4792.4 1916.90  4917.4 1915.73  4968.4 1912.29
  5009.1 1911.45  5011.4 1910.66  5011.7 1910.16  5015.4 1910.66  5089.6 1914.76
  5160.1 1916.01  5180.2 1917.13  5210.4 1916.07  5250.6 1917.38  5276.2 1916.95
  5321.0 1915.22  5331.1 1912.52  5341.2 1913.00  5375.7 1912.12  5381.4 1913.64
  5401.5 1915.90  5532.3 1919.68  5542.4 1920.84  5633.0 1921.81  5665.7 1922.98
#Mann=4,-1,0
  4602.0    0.07       0  5011.4    0.07       0  5015.4    0.07       0
  5276.2    0.16       0
Bank Sta=5011.4,5015.4
Exp/Cntr=0.3,0.1

Type RM Length L Ch R = 1,18914,289,289,289
BEGIN DESCRIPTION:
Elm 01 12 18913.84
END DESCRIPTION:
XS GIS Cut Line= 3
      1555658.36      6800790.05      1555616.69      6800352.52
      1555767.73      6799764.00
#Sta/Elev= 30
  4544.6 1919.18  4566.8 1917.16  4627.0 1914.23  4677.3 1914.82  4735.4 1913.51
  4918.3 1912.12  4938.4 1910.89  4946.3 1909.45  4958.5 1909.50  4983.9 1905.09
  4998.8 1904.67  4999.1 1904.17  5002.8 1904.67  5019.8 1905.00  5030.1 1906.27
  5036.4 1908.44  5041.6 1908.42  5050.7 1911.46  5164.3 1911.24  5267.5 1915.80
  5391.4 1918.61  5422.4 1922.79  5432.7 1921.97  5438.9 1923.12  5474.0 1924.67
  5479.7 1923.87  5484.8 1924.81  5515.3 1925.77  5536.0 1927.90  5591.7 1929.45
#Mann=3,-1,0
  4544.6    0.07       0  4998.8    0.07       0  5002.8    0.07       0
Bank Sta=4998.8,5002.8
Exp/Cntr=0.3,0.1

Type RM Length L Ch R = 1,18625,198,198,198
BEGIN DESCRIPTION:
Elm 01 12 18624.89
END DESCRIPTION:
XS GIS Cut Line= 3
      1555731.29      6800800.39      1555892.74      6800300.44
      1555939.46      6799781.31
#Sta/Elev= 30
  4462.2 1915.62  4506.7 1913.19  4538.3 1913.01  4580.3 1911.26  4769.5 1908.46
  4832.5 1908.87  4848.4 1910.22  4864.0 1909.20  4912.5 1909.58  4917.7 1910.47
  4937.6 1908.95  4949.7 1907.21  4981.8 1904.98  5000.1 1905.45  5008.1 1904.92
  5008.4 1904.42  5012.1 1904.92  5020.1 1905.56  5080.4 1905.93  5090.4 1907.84
  5110.5 1913.62  5120.5 1915.03  5130.6 1915.34  5160.7 1919.18  5190.8 1921.19
  5301.3 1925.73  5311.3 1927.26  5321.4 1927.68  5461.9 1931.39  5508.8 1933.64
#Mann=3,-1,0
  4462.2    0.07       0  5008.1    0.07       0  5012.1    0.07       0
Bank Sta=5008.1,5012.1
Exp/Cntr=0.3,0.1

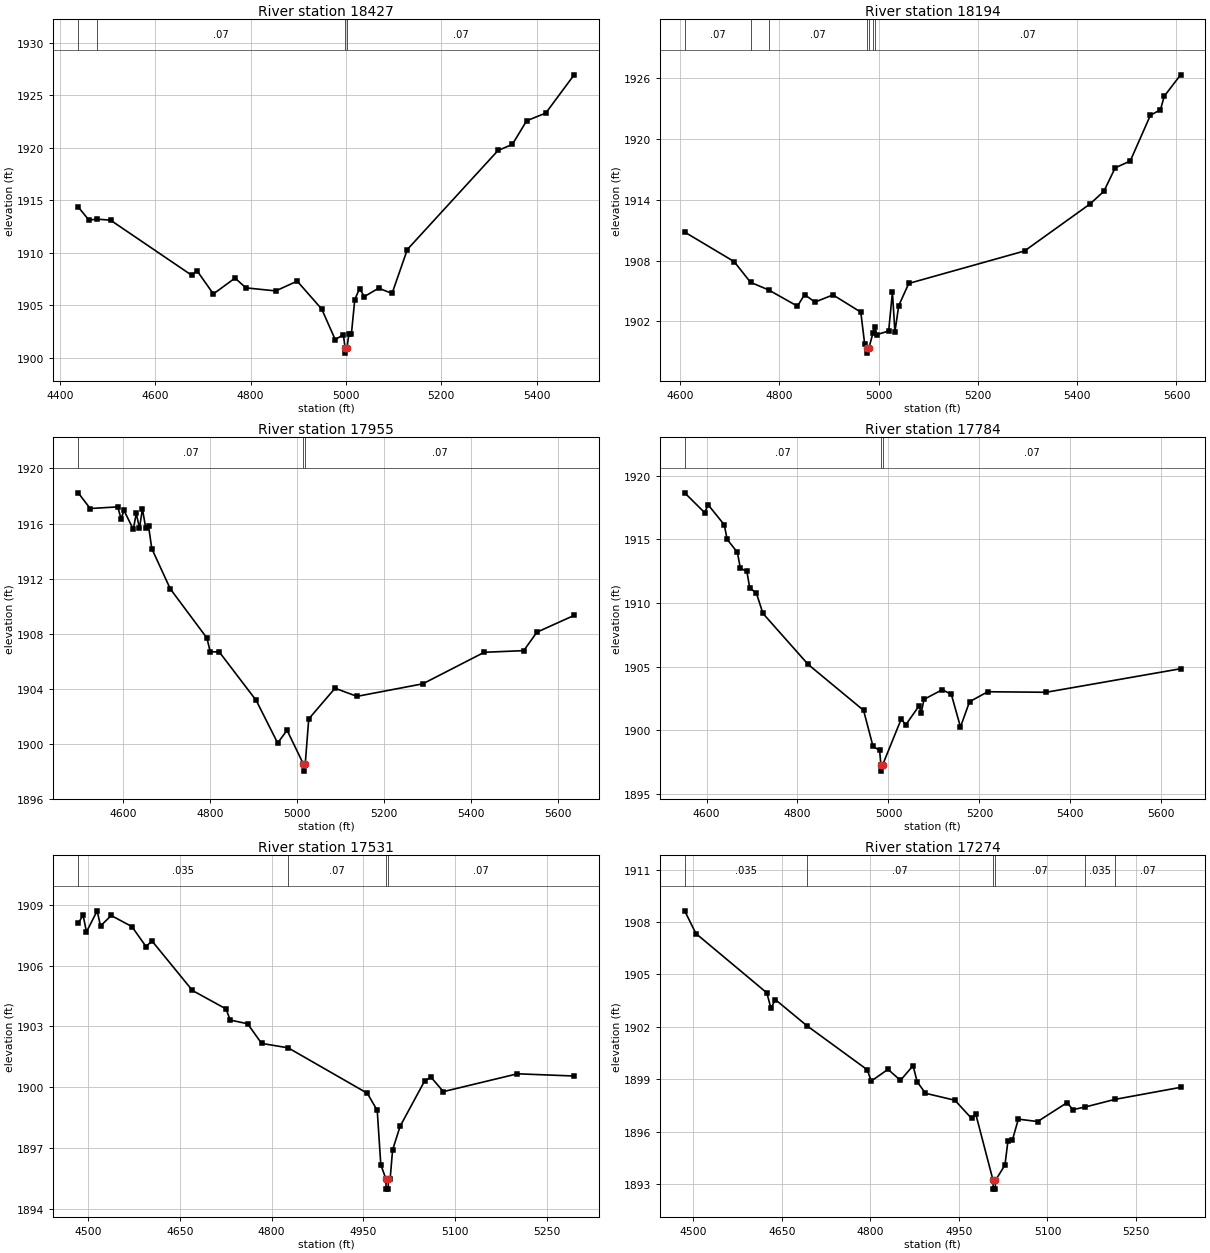
Type RM Length L Ch R = 1,18427,233,233,233
BEGIN DESCRIPTION:
Elm 01 12 18427.3
END DESCRIPTION:
XS GIS Cut Line= 3
      1555830.25      6800862.91      1556075.03      6800347.31
      1556048.99      6799878.59
#Sta/Elev= 30
  4438.4 1914.36  4460.8 1913.11  4478.1 1913.20  4506.2 1913.10  4676.4 1907.86
  4687.4 1908.30  4721.9 1906.08  4767.3 1907.59  4790.1 1906.66  4852.7 1906.37
  4897.7 1907.30  4949.2 1904.64  4977.4 1901.74  4994.6 1902.20  4998.1 1900.95
  4998.4 1900.45  5002.1 1900.95  5006.0 1902.23  5011.3 1902.23  5018.5 1905.55
  5028.5 1906.59  5038.5 1905.83  5068.6 1906.63  5096.7 1906.13  5128.7 1910.31
  5318.9 1919.73  5349.0 1920.31  5379.0 1922.56  5419.1 1923.29  5478.6 1926.93
#Mann=4,-1,0
  4438.4   0.035       0  4478.1    0.07       0  4998.1    0.07       0
  5002.1    0.07       0
Bank Sta=4998.1,5002.1
Exp/Cntr=0.3,0.1

Type RM Length L Ch R = 1,18194,239,239,239
BEGIN DESCRIPTION:
Elm 01 12 18194.398
END DESCRIPTION:
XS GIS Cut Line= 3
      1556005.01      6800787.99      1556255.00      6800488.00
      1556155.00      6799887.98
#Sta/Elev= 30
  4609.5 1910.81  4709.1 1907.90  4742.1 1905.86  4778.5 1905.11  4836.6 1903.51
  4851.0 1904.65  4871.8 1903.91  4908.2 1904.62  4964.2 1902.92  4972.0 1899.77
  4976.5 1899.38  4976.8 1898.88  4980.5 1899.38  4988.5 1900.83  4992.4 1901.49
  4996.7 1900.71  5020.3 1901.06  5027.9 1904.88  5032.9 1900.97  5040.6 1903.56
  5060.8 1905.75  5294.0 1908.95  5425.8 1913.58  5453.7 1914.83  5476.5 1917.14
  5506.9 1917.82  5547.4 1922.32  5567.7 1922.87  5575.3 1924.20  5608.3 1926.31
#Mann=7,-1,0
  4609.5    0.07       0  4742.1    0.16       0  4778.5    0.07       0
  4976.5    0.07       0  4980.5    0.07       0  4988.5    0.16       0
  4992.4    0.07       0
Bank Sta=4976.5,4980.5
Exp/Cntr=0.3,0.1

Type RM Length L Ch R = 1,17955,171,171,171
BEGIN DESCRIPTION:
Elm 01 12 17954.96
END DESCRIPTION:
XS GIS Cut Line= 3
      1556101.09      6800993.12      1556444.82      6800623.35
      1556356.27      6799993.10
#Sta/Elev= 30
  4497.0 1918.23  4524.6 1917.09  4588.1 1917.21  4595.5 1916.34  4602.3 1916.95
  4623.8 1915.58  4630.6 1916.74  4638.0 1915.67  4644.8 1917.06  4652.2 1915.71
  4659.0 1915.79  4666.3 1914.18  4708.8 1911.26  4793.3 1907.68  4800.7 1906.69
  4821.7 1906.67  4906.7 1903.15  4956.0 1900.06  4977.6 1900.99  5015.4 1898.52
  5015.6 1898.02  5019.4 1898.52  5027.5 1901.81  5088.0 1904.04  5138.5 1903.45
  5290.0 1904.36  5431.4 1906.65  5522.3 1906.77  5552.6 1908.11  5638.3 1909.33
#Mann=3,-1,0
  4497.0    0.07       0  5015.4    0.07       0  5019.4    0.07       0
Bank Sta=5015.4,5019.4
Exp/Cntr=0.3,0.1

Type RM Length L Ch R = 1,17784,253,253,253
BEGIN DESCRIPTION:
Elm 01 12 17784.14
END DESCRIPTION:
XS GIS Cut Line= 3
      1556325.05      6801039.99      1556595.86      6800696.27
      1556548.99      6800045.24
#Sta/Elev= 30
  4552.0 1918.66  4595.7 1917.11  4603.8 1917.71  4639.0 1916.15  4645.4 1915.00
  4667.9 1913.98  4674.3 1912.74  4688.7 1912.48  4695.1 1911.17  4709.5 1910.79
  4724.0 1909.18  4823.4 1905.17  4945.3 1901.56  4966.1 1898.72  4980.6 1898.41
  4983.3 1897.28  4983.5 1896.78  4987.3 1897.28  5028.0 1900.87  5038.0 1900.42
  5067.1 1901.90  5072.1 1901.36  5078.1 1902.42  5118.2 1903.18  5138.2 1902.82
  5158.3 1900.25  5178.3 1902.24  5218.4 1903.02  5346.7 1902.98  5642.3 1904.83
#Mann=3,-1,0
  4552.0    0.07       0  4983.3    0.07       0  4987.3    0.07       0
Bank Sta=4983.3,4987.3
Exp/Cntr=0.3,0.1

Type RM Length L Ch R = 1,17531,257,257,257
BEGIN DESCRIPTION:
Elm 01 12 17530.48
END DESCRIPTION:
XS GIS Cut Line= 3
      1556585.45      6801107.72      1556798.99      6800644.19
      1556842.75      6800346.24
#Sta/Elev= 30
  4483.6 1908.08  4491.6 1908.49  4497.1 1907.66  4514.6 1908.70  4520.1 1907.95
  4537.6 1908.47  4571.5 1907.92  4594.5 1906.94  4604.4 1907.21  4670.5 1904.77
  4725.5 1903.86  4732.3 1903.31  4760.7 1903.13  4783.7 1902.16  4827.2 1901.94
  4956.7 1899.70  4972.9 1898.85  4978.7 1896.18  4987.1 1895.47  4987.4 1894.97
  4990.9 1894.97  4991.1 1895.47  4994.0 1895.47  4998.0 1896.90  5010.3 1898.07
  5050.7 1900.32  5060.9 1900.49  5081.1 1899.78  5202.3 1900.66  5295.1 1900.55
#Mann=4,-1,0
  4483.6   0.035       0  4827.2    0.07       0  4987.1    0.07       0
  4991.1    0.07       0
Bank Sta=4987.1,4991.1
Exp/Cntr=0.3,0.1

Type RM Length L Ch R = 1,17274,241,241,241
BEGIN DESCRIPTION:
Elm 01 12 17272.2
END DESCRIPTION:
XS GIS Cut Line= 3
      1556663.60      6801123.32      1557012.53      6800753.56
      1557079.78      6800428.96
#Sta/Elev= 30
  4485.6 1908.64  4504.6 1907.34  4624.8 1903.94  4631.7 1903.05  4639.0 1903.56
  4692.2 1902.07  4794.7 1899.54  4801.6 1898.89  4829.9 1899.56  4851.0 1898.93
  4872.4 1899.77  4879.3 1898.85  4893.4 1898.19  4943.2 1897.79  4971.5 1896.75
  4978.4 1897.02  5007.9 1893.20  5008.1 1892.70  5011.6 1892.70  5011.9 1893.20
  5028.0 1894.08  5033.1 1895.47  5040.5 1895.50  5050.7 1896.71  5083.3 1896.57
  5133.5 1897.66  5142.7 1897.25  5163.5 1897.40  5214.2 1897.84  5325.5 1898.53
#Mann=6,-1,0
  4485.6   0.035       0  4692.2    0.07       0  5007.9    0.07       0
  5011.9    0.07       0  5163.5   0.035       0  5214.2    0.07       0
Bank Sta=5007.9,5011.9
Exp/Cntr=0.3,0.1

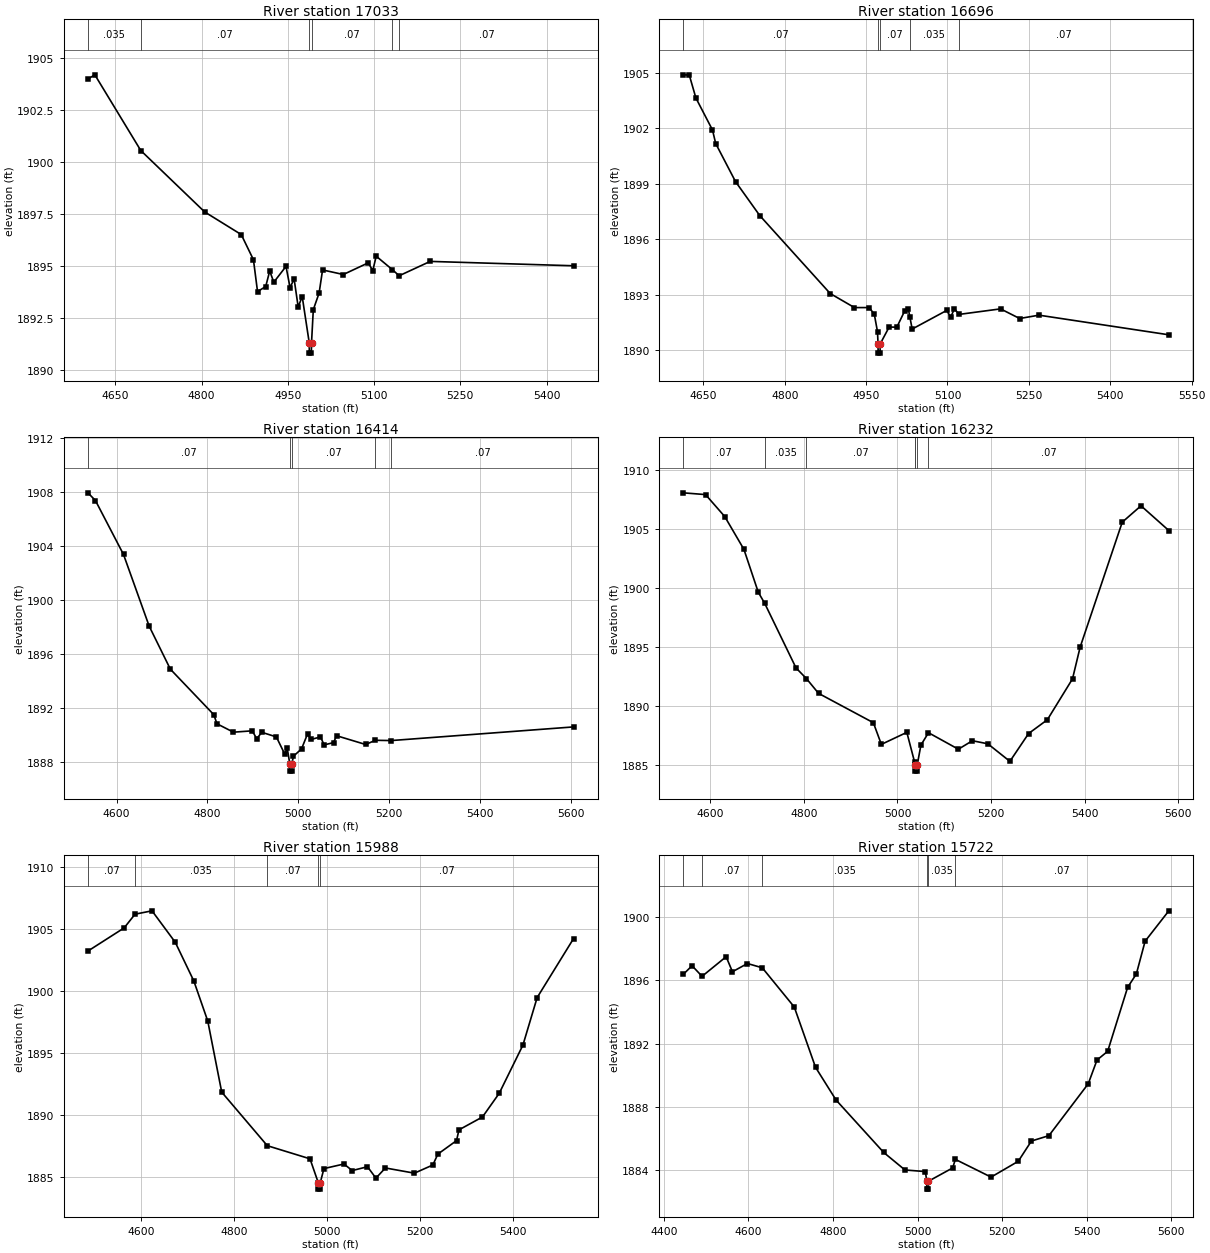
Type RM Length L Ch R = 1,17033,337,337,337
BEGIN DESCRIPTION:
Elm 01 12 17032.94
END DESCRIPTION:
XS GIS Cut Line= 3
      1556871.89      6801211.91      1557153.15      6800935.85
      1557401.23      6800559.93
#Sta/Elev= 30
  4602.5 1903.99  4614.5 1904.19  4694.4 1900.55  4805.4 1897.60  4869.1 1896.51
  4890.3 1895.30  4897.4 1893.77  4911.6 1894.01  4918.6 1894.76  4925.7 1894.22
  4946.9 1894.98  4954.0 1893.96  4961.0 1894.38  4968.1 1893.03  4975.1 1893.53
  4987.3 1891.31  4987.5 1890.81  4991.0 1890.81  4991.3 1891.31  4994.4 1892.90
  5004.5 1893.70  5010.5 1894.81  5046.6 1894.59  5089.9 1895.15  5097.8 1894.78
  5103.8 1895.47  5131.6 1894.83  5143.7 1894.53  5197.7 1895.22  5447.0 1895.01
#Mann=6,-1,0
  4602.5   0.035       0  4694.4    0.07       0  4987.3    0.07       0
  4991.3    0.07       0  5131.6   0.035       0  5143.7    0.07       0
Bank Sta=4987.3,4991.3
Exp/Cntr=0.3,0.1

Type RM Length L Ch R = 1,16696,282,282,282
BEGIN DESCRIPTION:
Elm 01 12 16695.97
END DESCRIPTION:
XS GIS Cut Line= 3
      1557085.48      6801352.50      1557392.74      6801159.81
      1557761.28      6800775.70
#Sta/Elev= 30
  4612.9 1904.88  4624.1 1904.87  4636.3 1903.63  4666.9 1901.90  4672.8 1901.17
  4709.4 1899.11  4754.0 1897.28  4883.8 1893.07  4928.5 1892.31  4955.7 1892.31
  4965.1 1891.95  4971.0 1891.01  4972.0 1890.35  4972.2 1889.85  4975.7 1889.85
  4976.0 1890.35  4992.5 1891.26  5006.6 1891.25  5020.8 1892.11  5028.0 1892.21
  5030.8 1891.78  5034.9 1891.15  5098.8 1892.16  5105.7 1891.79  5112.9 1892.25
  5121.0 1891.94  5197.8 1892.24  5233.0 1891.72  5268.6 1891.90  5507.9 1890.84
#Mann=5,-1,0
  4612.9    0.07       0  4972.0    0.07       0  4976.0    0.07       0
  5030.8   0.035       0  5121.0    0.07       0
Bank Sta=4972,4976
Exp/Cntr=0.3,0.1

Type RM Length L Ch R = 1,16414,182,182,182
BEGIN DESCRIPTION:
Elm 01 12 16412.81
END DESCRIPTION:
XS GIS Cut Line= 3
      1557173.98      6801498.36      1557601.07      6801347.31
      1558085.63      6800966.83
#Sta/Elev= 30
  4536.9 1907.91  4553.4 1907.34  4615.2 1903.35  4671.7 1898.05  4718.3 1894.87
  4813.8 1891.51  4821.0 1890.83  4857.2 1890.21  4898.6 1890.31  4908.4 1889.73
  4919.8 1890.20  4951.7 1889.86  4970.2 1888.58  4975.5 1889.04  4981.5 1887.83
  4981.7 1887.33  4985.2 1887.33  4985.5 1887.83  4989.3 1888.43  5007.2 1888.98
  5020.3 1890.08  5028.0 1889.67  5048.8 1889.86  5056.9 1889.27  5077.7 1889.44
  5084.1 1889.95  5148.2 1889.30  5169.7 1889.61  5204.5 1889.59  5606.0 1890.60
#Mann=5,-1,0
  4536.9    0.07       0  4981.5    0.07       0  4985.5    0.07       0
  5169.7   0.035       0  5204.5    0.07       0
Bank Sta=4981.5,4985.5
Exp/Cntr=0.3,0.1

Type RM Length L Ch R = 1,16232,244,244,244
BEGIN DESCRIPTION:
Elm 01 12 16231.85
END DESCRIPTION:
XS GIS Cut Line= 3
      1557158.37      6801597.31      1557616.69      6801493.14
      1558184.42      6801524.40
#Sta/Elev= 30
  4541.7 1908.07  4589.5 1907.92  4630.5 1906.06  4671.6 1903.27  4702.3 1899.63
  4715.9 1898.70  4783.0 1893.21  4805.3 1892.30  4831.2 1891.05  4948.4 1888.56
  4965.5 1886.72  5020.0 1887.74  5036.7 1885.20  5038.1 1884.95  5038.3 1884.45
  5041.8 1884.45  5042.1 1884.95  5050.1 1886.66  5066.3 1887.71  5130.2 1886.31
  5160.2 1887.03  5193.2 1886.77  5240.4 1885.28  5280.4 1887.64  5320.5 1888.81
  5374.3 1892.28  5390.6 1894.97  5480.7 1905.58  5520.8 1906.97  5580.3 1904.87
#Mann=7,-1,0
  4541.7    0.07       0  4715.9   0.035       0  4805.3    0.07       0
  5036.7   0.035       0  5038.1    0.07       0  5042.1   0.035       0
  5066.3    0.07       0
Bank Sta=5038.1,5042.1
Exp/Cntr=0.3,0.1

Type RM Length L Ch R = 1,15988,266,266,266
BEGIN DESCRIPTION:
Elm 01 12 15987.79
END DESCRIPTION:
XS GIS Cut Line= 3
      1557127.10      6801727.52      1557653.15      6801727.52
      1558161.82      6801623.71
#Sta/Elev= 30
  4484.9 1903.22  4562.8 1905.09  4586.3 1906.20  4622.8 1906.47  4672.8 1903.93
  4712.8 1900.80  4742.8 1897.56  4772.8 1891.82  4870.9 1887.49  4962.8 1886.43
  4980.8 1884.48  4981.0 1883.98  4984.5 1883.98  4984.8 1884.48  4992.8 1885.64
  5035.9 1886.01  5053.7 1885.48  5086.5 1885.79  5104.7 1884.87  5125.1 1885.69
  5187.5 1885.27  5227.2 1885.93  5238.0 1886.81  5278.2 1887.90  5283.4 1888.77
  5334.0 1889.81  5370.0 1891.72  5421.1 1895.62  5451.7 1899.46  5530.1 1904.23
#Mann=5,-1,0
  4484.9    0.07       0  4586.3   0.035       0  4870.9    0.07       0
  4980.8    0.07       0  4984.8    0.07       0
Bank Sta=4980.8,4984.8
Exp/Cntr=0.3,0.1

Type RM Length L Ch R = 1,15722,229,229,229
BEGIN DESCRIPTION:
Elm 01 12 15722.31
END DESCRIPTION:
XS GIS Cut Line= 3
      1557054.16      6801888.97      1557611.49      6801956.69
      1558179.21      6801805.64
#Sta/Elev= 30
  4445.6 1896.37  4466.6 1896.92  4490.2 1896.25  4547.2 1897.49  4562.1 1896.54
  4597.6 1897.06  4632.7 1896.79  4708.4 1894.31  4758.7 1890.50  4807.3 1888.43
  4919.9 1885.12  4970.3 1884.01  5018.6 1883.91  5021.8 1883.30  5022.0 1882.80
  5025.5 1882.80  5025.8 1883.30  5083.1 1884.14  5089.5 1884.68  5174.0 1883.56
  5238.3 1884.56  5269.4 1885.84  5310.8 1886.18  5403.9 1889.46  5424.6 1890.96
  5449.8 1891.51  5497.0 1895.55  5517.7 1896.40  5538.4 1898.47  5594.5 1900.39
#Mann=6,-1,0
  4445.6   0.035       0  4490.2    0.07       0  4632.7   0.035       0
  5021.8   0.035       0  5025.8   0.035       0  5089.5    0.07       0
Bank Sta=5021.8,5025.8
Exp/Cntr=0.3,0.1