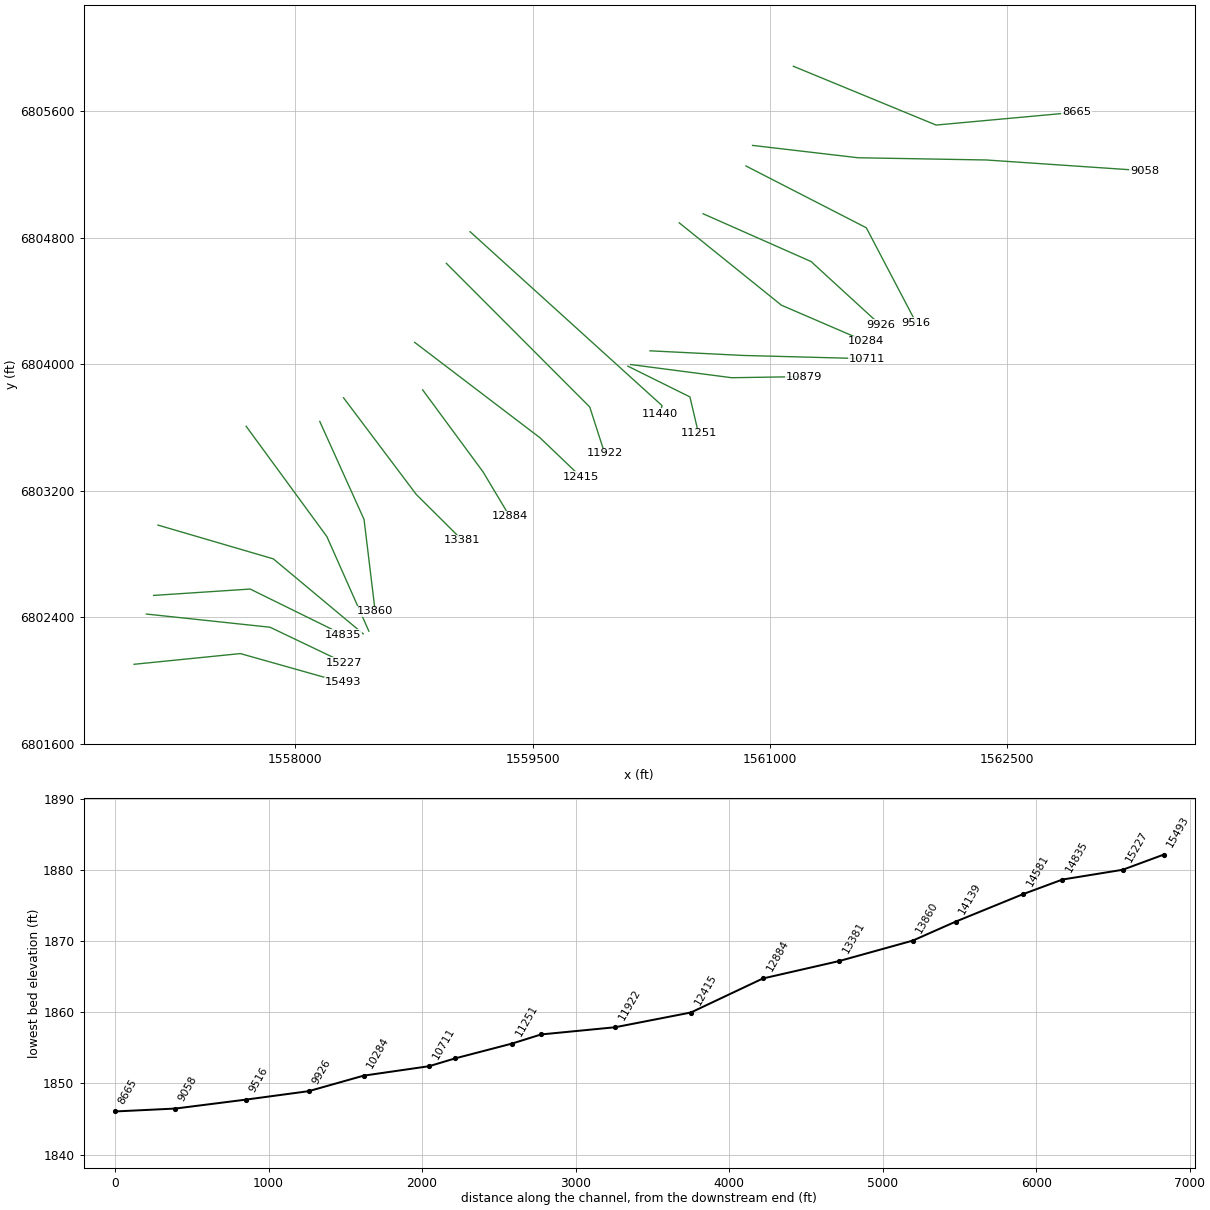
HEC-RAS study Elm 01 12.prj: Elm 01 12 Base Level Engineering

--- Elm 01 12.g01 (geometry) --- (continued)

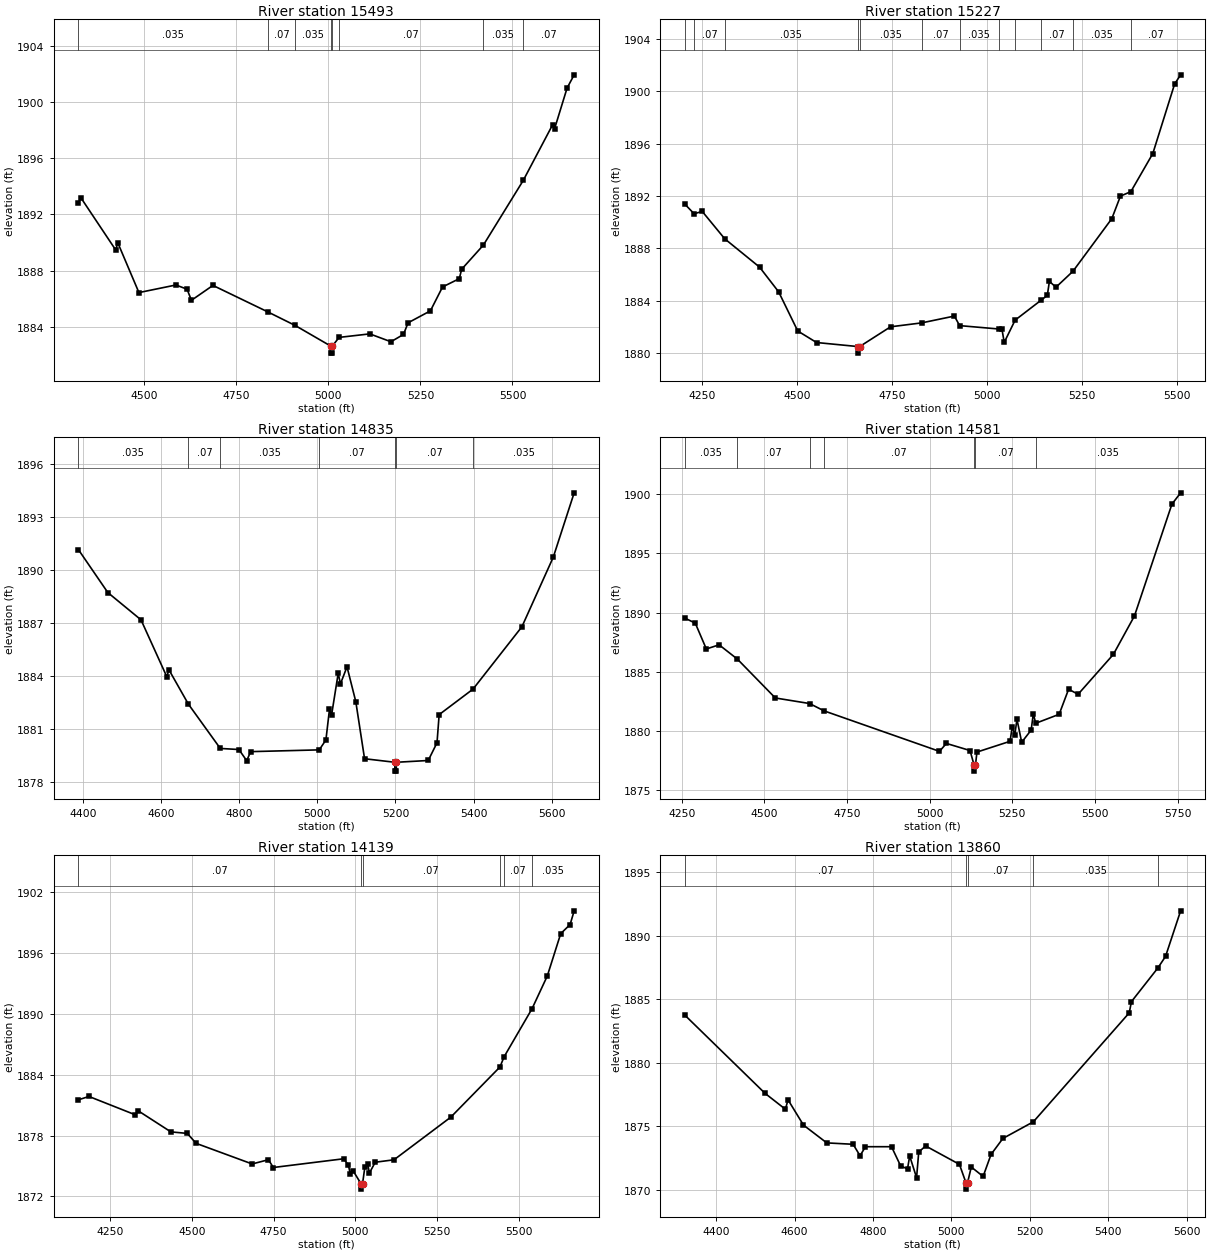
Type RM Length L Ch R = 1,15493,266,266,266
BEGIN DESCRIPTION:
Elm 01 12 15493.15
END DESCRIPTION:
XS GIS Cut Line= 3
      1556981.33      6802102.52      1557653.15      6802170.23
      1558298.99      6801987.94
#Sta/Elev= 30
  4321.2 1892.82  4327.9 1893.20  4423.0 1889.46  4428.1 1890.00  4485.7 1886.44
  4586.2 1886.98  4616.4 1886.68  4628.3 1885.89  4686.7 1886.95  4835.3 1885.07
  4909.9 1884.10  5006.7 1882.63  5007.0 1882.13  5010.5 1882.13  5010.7 1882.63
  5029.3 1883.25  5112.6 1883.50  5170.0 1882.94  5204.0 1883.46  5216.6 1884.29
  5277.2 1885.14  5310.1 1886.84  5355.6 1887.43  5362.0 1888.10  5421.0 1889.82
  5529.2 1894.42  5609.1 1898.39  5614.3 1898.10  5648.3 1901.00  5667.5 1901.94
#Mann=8,-1,0
  4321.2   0.035       0  4835.3    0.07       0  4909.9   0.035       0
  5006.7   0.035       0  5010.7   0.035       0  5029.3    0.07       0
  5421.0   0.035       0  5529.2    0.07       0
Bank Sta=5006.7,5010.7
Exp/Cntr=0.3,0.1

Type RM Length L Ch R = 1,15227,392,392,392
BEGIN DESCRIPTION:
Elm 01 12 15227.26
END DESCRIPTION:
XS GIS Cut Line= 3
      1557059.37      6802420.23      1557840.65      6802336.89
      1558309.29      6802112.99
#Sta/Elev= 30
  4204.3 1891.39  4228.8 1890.65  4250.2 1890.83  4309.4 1888.74  4401.0 1886.58
  4451.3 1884.69  4501.6 1881.70  4551.1 1880.82  4660.5 1880.51  4660.8 1880.01
  4664.5 1880.51  4745.9 1882.02  4827.9 1882.32  4913.9 1882.84  4927.7 1882.11
  5031.8 1881.85  5039.2 1881.82  5045.1 1880.83  5073.8 1882.53  5143.0 1884.07
  5158.5 1884.42  5164.0 1885.49  5181.2 1885.04  5226.0 1886.26  5328.3 1890.28
  5351.0 1892.00  5378.4 1892.34  5436.2 1895.25  5493.6 1900.56  5509.4 1901.26
#Mann=12,-1,0
  4204.3   0.035       0  4228.8    0.07       0  4309.4   0.035       0
  4660.5   0.035       0  4664.5   0.035       0  4827.9    0.07       0
  4927.7   0.035       0  5031.8    0.07       0  5073.8   0.035       0
  5143.0    0.07       0  5226.0   0.035       0  5378.4    0.07       0
Bank Sta=4660.5,4664.5
Exp/Cntr=0.3,0.1

Type RM Length L Ch R = 1,14835,254,254,254
BEGIN DESCRIPTION:
Elm 01 12 14834.713
END DESCRIPTION:
XS GIS Cut Line= 3
      1557104.99      6802538.00      1557715.16      6802578.30
      1558304.99      6802288.00
#Sta/Elev= 30
  4388.5 1891.15  4464.0 1888.72  4548.9 1887.18  4615.1 1883.96  4620.1 1884.37
  4670.2 1882.42  4751.8 1879.92  4799.4 1879.86  4819.4 1879.23  4829.5 1879.74
  5005.0 1879.84  5022.1 1880.40  5031.2 1882.12  5036.7 1881.82  5053.6 1884.17
  5059.2 1883.56  5076.1 1884.53  5098.6 1882.56  5121.0 1879.34  5198.4 1879.14
  5198.7 1878.64  5202.2 1878.64  5202.4 1879.14  5283.9 1879.24  5306.4 1880.24
  5311.9 1881.83  5398.6 1883.27  5523.7 1886.79  5604.0 1890.72  5657.4 1894.35
#Mann=7,-1,0
  4388.5   0.035       0  4670.2    0.07       0  4751.8   0.035       0
  5005.0    0.07       0  5198.4   0.035       0  5202.4    0.07       0
  5398.6   0.035       0
Bank Sta=5198.4,5202.4
Exp/Cntr=0.3,0.1

Type RM Length L Ch R = 1,14581,442,442,442
BEGIN DESCRIPTION:
Elm 01 12 14580.56
END DESCRIPTION:
XS GIS Cut Line= 3
      1557132.34      6802982.72      1557861.49      6802769.19
      1558429.18      6802295.24
#Sta/Elev= 30
  4259.5 1889.54  4291.2 1889.11  4324.6 1886.93  4363.3 1887.28  4418.6 1886.07
  4533.2 1882.79  4636.8 1882.32  4680.7 1881.70  5029.6 1878.28  5050.5 1878.95
  5122.0 1878.35  5134.4 1877.11  5134.6 1876.61  5138.4 1877.11  5142.9 1878.22
  5243.1 1879.13  5249.6 1880.37  5257.4 1879.68  5263.9 1880.99  5278.2 1879.05
  5306.9 1880.08  5313.4 1881.47  5320.4 1880.65  5391.5 1881.41  5420.1 1883.53
  5448.7 1883.10  5555.4 1886.47  5619.2 1889.72  5732.4 1899.16  5758.8 1900.12
#Mann=7,-1,0
  4259.5   0.035       0  4418.6    0.07       0  4636.8   0.035       0
  4680.7    0.07       0  5134.4    0.07       0  5138.4    0.07       0
  5320.4   0.035       0
Bank Sta=5134.4,5138.4
Exp/Cntr=0.3,0.1

Type RM Length L Ch R = 1,14139,279,279,279
BEGIN DESCRIPTION:
Elm 01 12 14139.11
END DESCRIPTION:
XS GIS Cut Line= 3
      1557689.60      6803607.74      1558200.03      6802909.81
      1558465.18      6802311.93
#Sta/Elev= 30
  4151.7 1881.52  4184.3 1881.85  4326.4 1880.04  4334.9 1880.44  4435.2 1878.36
  4485.4 1878.21  4512.5 1877.23  4684.1 1875.20  4734.1 1875.62  4748.8 1874.85
  4964.2 1875.71  4978.8 1875.10  4985.0 1874.17  4993.5 1874.52  5018.1 1873.22
  5018.3 1872.72  5022.1 1873.22  5029.3 1874.89  5037.9 1875.18  5043.3 1874.31
  5061.1 1875.37  5118.6 1875.61  5292.5 1879.81  5443.0 1884.75  5456.0 1885.77
  5541.3 1890.49  5588.1 1893.72  5629.2 1897.89  5658.0 1898.79  5670.4 1900.14
#Mann=6,-1,0
  4151.7    0.07       0  5018.1    0.07       0  5022.1    0.07       0
  5443.0   0.035       0  5456.0    0.07       0  5541.3   0.035       0
Bank Sta=5018.1,5022.1
Exp/Cntr=0.3,0.1

Type RM Length L Ch R = 1,13860,479,479,479
BEGIN DESCRIPTION:
Elm 01 12 13859.63
END DESCRIPTION:
XS GIS Cut Line= 3
      1558155.01      6803637.99      1558434.86      6803018.35
      1558505.00      6802437.98
#Sta/Elev= 30
  4320.1 1883.76  4524.8 1877.60  4576.6 1876.35  4583.4 1877.09  4622.8 1875.10
  4682.2 1873.70  4749.4 1873.59  4767.0 1872.69  4780.9 1873.40  4847.3 1873.40
  4870.5 1871.89  4888.1 1871.65  4893.6 1872.67  4911.2 1870.96  4916.7 1872.98
  4934.3 1873.46  5020.5 1872.01  5037.2 1870.56  5037.5 1870.06  5041.2 1870.56
  5050.7 1871.80  5080.9 1871.06  5101.1 1872.79  5131.3 1874.05  5209.0 1875.36
  5453.6 1883.94  5459.1 1884.82  5526.3 1887.46  5546.1 1888.38  5584.6 1891.97
#Mann=5,-1,0
  4320.1    0.07       0  5037.2    0.07       0  5041.2    0.07       0
  5209.0   0.035       0  5526.3    0.07       0
Bank Sta=5037.2,5041.2
Exp/Cntr=0.3,0.1

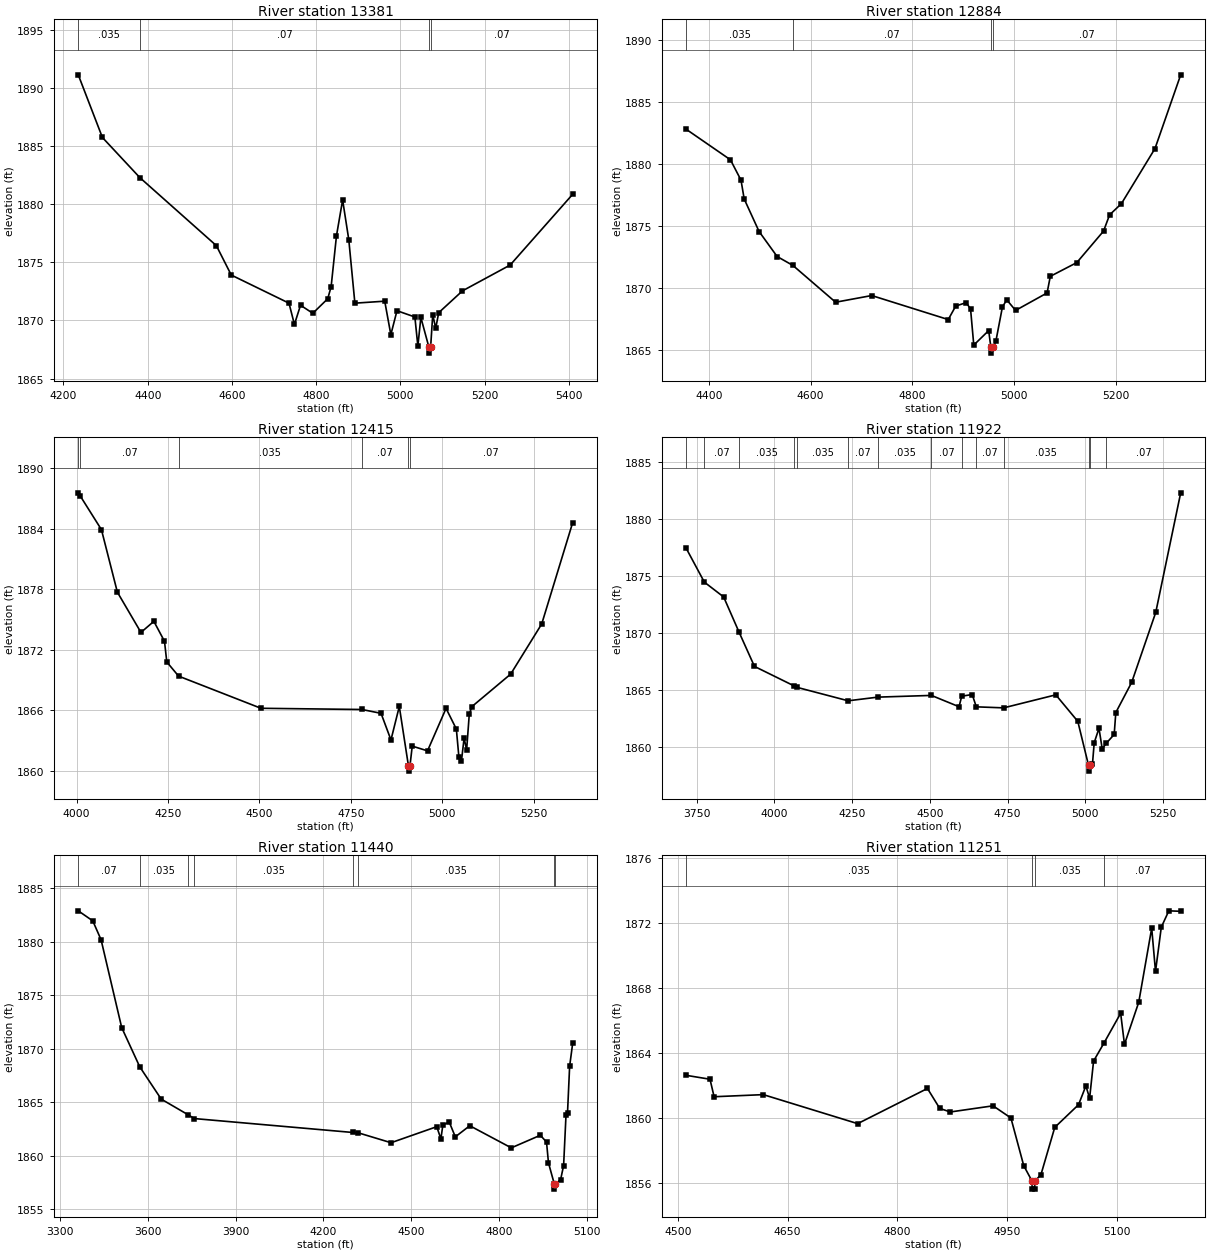
Type RM Length L Ch R = 1,13381,497,497,497
BEGIN DESCRIPTION:
Elm 01 12 13380.996
END DESCRIPTION:
XS GIS Cut Line= 3
      1558305.00      6803788.00      1558764.72      6803176.67
      1559055.01      6802887.99
#Sta/Elev= 30
  4235.1 1891.14  4292.4 1885.75  4381.5 1882.29  4563.1 1876.44  4598.5 1873.91
  4735.6 1871.49  4748.5 1869.66  4763.0 1871.31  4792.2 1870.62  4827.6 1871.87
  4835.7 1872.91  4848.4 1877.29  4863.0 1880.37  4877.6 1876.96  4892.1 1871.49
  4963.0 1871.66  4977.5 1868.78  4992.1 1870.84  5034.6 1870.30  5041.7 1867.79
  5048.8 1870.26  5068.0 1867.69  5068.2 1867.19  5072.0 1867.69  5077.0 1870.50
  5084.1 1869.33  5091.2 1870.67  5147.7 1872.55  5260.9 1874.77  5409.4 1880.86
#Mann=4,-1,0
  4235.1   0.035       0  4381.5    0.07       0  5068.0    0.07       0
  5072.0    0.07       0
Bank Sta=5068,5072
Exp/Cntr=0.3,0.1

Type RM Length L Ch R = 1,12884,469,469,469
BEGIN DESCRIPTION:
Elm 01 12 12884.11
END DESCRIPTION:
XS GIS Cut Line= 3
      1558804.98      6803838.02      1559186.90      6803319.12
      1559354.98      6803038.04
#Sta/Elev= 30
  4355.7 1882.81  4442.5 1880.35  4463.3 1878.70  4469.5 1877.19  4498.8 1874.56
  4534.3 1872.54  4565.3 1871.82  4649.2 1868.85  4720.2 1869.39  4870.6 1867.45
  4885.3 1868.54  4906.1 1868.82  4914.5 1868.29  4920.8 1865.39  4950.1 1866.56
  4954.3 1865.24  4954.5 1864.74  4958.3 1865.24  4964.1 1865.68  4977.1 1868.47
  4985.6 1869.04  5003.0 1868.19  5064.9 1869.60  5071.2 1870.94  5123.3 1872.05
  5175.8 1874.59  5187.7 1875.90  5211.0 1876.81  5277.0 1881.26  5327.5 1887.21
#Mann=4,-1,0
  4355.7   0.035       0  4565.3    0.07       0  4954.3    0.07       0
  4958.3    0.07       0
Bank Sta=4954.3,4958.3
Exp/Cntr=0.3,0.1

Type RM Length L Ch R = 1,12415,493,493,493
BEGIN DESCRIPTION:
Elm 01 12 12414.952
END DESCRIPTION:
XS GIS Cut Line= 3
      1558755.03      6804137.98      1559546.99      6803534.65
      1559804.98      6803288.02
#Sta/Elev= 30
  4004.4 1887.55  4009.3 1887.27  4067.8 1883.90  4111.4 1877.70  4175.9 1873.71
  4211.2 1874.81  4240.3 1872.83  4246.6 1870.78  4278.8 1869.38  4504.3 1866.19
  4780.4 1866.07  4832.7 1865.69  4859.8 1863.05  4882.6 1866.37  4907.7 1860.46
  4908.0 1859.96  4911.7 1860.46  4918.0 1862.44  4959.8 1861.97  5010.5 1866.18
  5038.7 1864.13  5045.7 1861.33  5052.6 1860.96  5059.9 1863.23  5066.8 1862.06
  5074.0 1865.59  5081.0 1866.35  5187.3 1869.58  5272.2 1874.55  5356.9 1884.60
#Mann=6,-1,0
  4004.4   0.035       0  4009.3    0.07       0  4278.8   0.035       0
  4780.4    0.07       0  4907.7    0.07       0  4911.7    0.07       0
Bank Sta=4907.7,4911.7
Exp/Cntr=0.3,0.1

Type RM Length L Ch R = 1,11922,482,482,482
BEGIN DESCRIPTION:
Elm 01 12 11922.327
END DESCRIPTION:
XS GIS Cut Line= 3
      1558955.03      6804637.97      1559861.18      6803729.55
      1559955.01      6803437.97
#Sta/Elev= 30
  3716.9 1877.39  3775.0 1874.44  3837.1 1873.14  3886.9 1870.04  3936.1 1867.06
  4063.7 1865.35  4072.3 1865.23  4237.2 1864.05  4333.0 1864.37  4504.9 1864.52
  4593.7 1863.53  4602.4 1864.45  4636.1 1864.60  4649.2 1863.52  4737.1 1863.43
  4904.8 1864.57  4975.5 1862.25  5010.1 1858.39  5010.4 1857.89  5014.1 1858.39
  5022.6 1858.49  5028.3 1860.38  5043.6 1861.64  5054.1 1859.83  5066.7 1860.32
  5092.5 1861.10  5097.7 1863.02  5148.7 1865.66  5226.1 1871.79  5306.3 1882.26
#Mann=14,-1,0
  3716.9   0.035       0  3775.0    0.07       0  3886.9   0.035       0
  4063.7    0.07       0  4072.3   0.035       0  4237.2    0.07       0
  4333.0   0.035       0  4504.9    0.07       0  4602.4   0.035       0
  4649.2    0.07       0  4737.1   0.035       0  5010.1   0.035       0
  5014.1   0.035       0  5066.7    0.07       0
Bank Sta=5010.1,5014.1
Exp/Cntr=0.3,0.1

Type RM Length L Ch R = 1,11440,189,189,189
BEGIN DESCRIPTION:
Elm 01 12 11439.772
END DESCRIPTION:
XS GIS Cut Line= 3
      1559105.02      6804837.98      1560318.18      6803738.29
      1560305.00      6803687.99
#Sta/Elev= 30
  3362.6 1882.91  3412.2 1881.97  3440.6 1880.20  3511.0 1871.99  3572.7 1868.32
  3646.0 1865.30  3736.4 1863.86  3759.1 1863.48  4300.1 1862.18  4317.7 1862.16
  4431.4 1861.22  4587.5 1862.72  4601.7 1861.58  4608.4 1862.87  4630.1 1863.16
  4651.0 1861.77  4700.4 1862.81  4842.3 1860.74  4941.6 1861.92  4962.6 1861.28
  4969.3 1859.34  4989.0 1857.38  4989.2 1856.88  4993.0 1857.38  5010.6 1857.75
  5021.0 1859.08  5029.2 1863.81  5034.4 1864.03  5041.6 1868.38  5052.0 1870.52
#Mann=8,-1,0
  3362.6    0.07       0  3572.7   0.035       0  3736.4    0.07       0
  3759.1   0.035       0  4300.1    0.07       0  4317.7   0.035       0
  4989.0   0.035       0  4993.0   0.035       0
Bank Sta=4989,4993
Exp/Cntr=0.3,0.1

Type RM Length L Ch R = 1,11251,372,372,372
BEGIN DESCRIPTION:
Elm 01 12 11165.4
END DESCRIPTION:
XS GIS Cut Line= 3
      1560101.94      6803987.85      1560494.25      6803793.31
      1560548.50      6803562.19
#Sta/Elev= 30
  4511.7 1862.62  4544.1 1862.38  4549.7 1861.30  4616.9 1861.43  4745.8 1859.64
  4841.1 1861.81  4857.9 1860.58  4872.3 1860.36  4930.7 1860.74  4955.1 1859.99
  4972.6 1857.05  4983.9 1856.10  4984.1 1855.60  4987.6 1855.60  4987.9 1856.10
  4996.1 1856.49  5015.0 1859.41  5047.5 1860.81  5057.5 1861.97  5062.6 1861.21
  5068.0 1863.50  5082.3 1864.62  5105.0 1866.45  5110.2 1864.53  5129.7 1867.13
  5147.4 1871.70  5152.6 1869.03  5160.5 1871.76  5170.8 1872.77  5187.0 1872.74
#Mann=4,-1,0
  4511.7   0.035       0  4983.9   0.035       0  4987.9   0.035       0
  5082.3    0.07       0
Bank Sta=4983.9,4987.9
Exp/Cntr=0.3,0.1

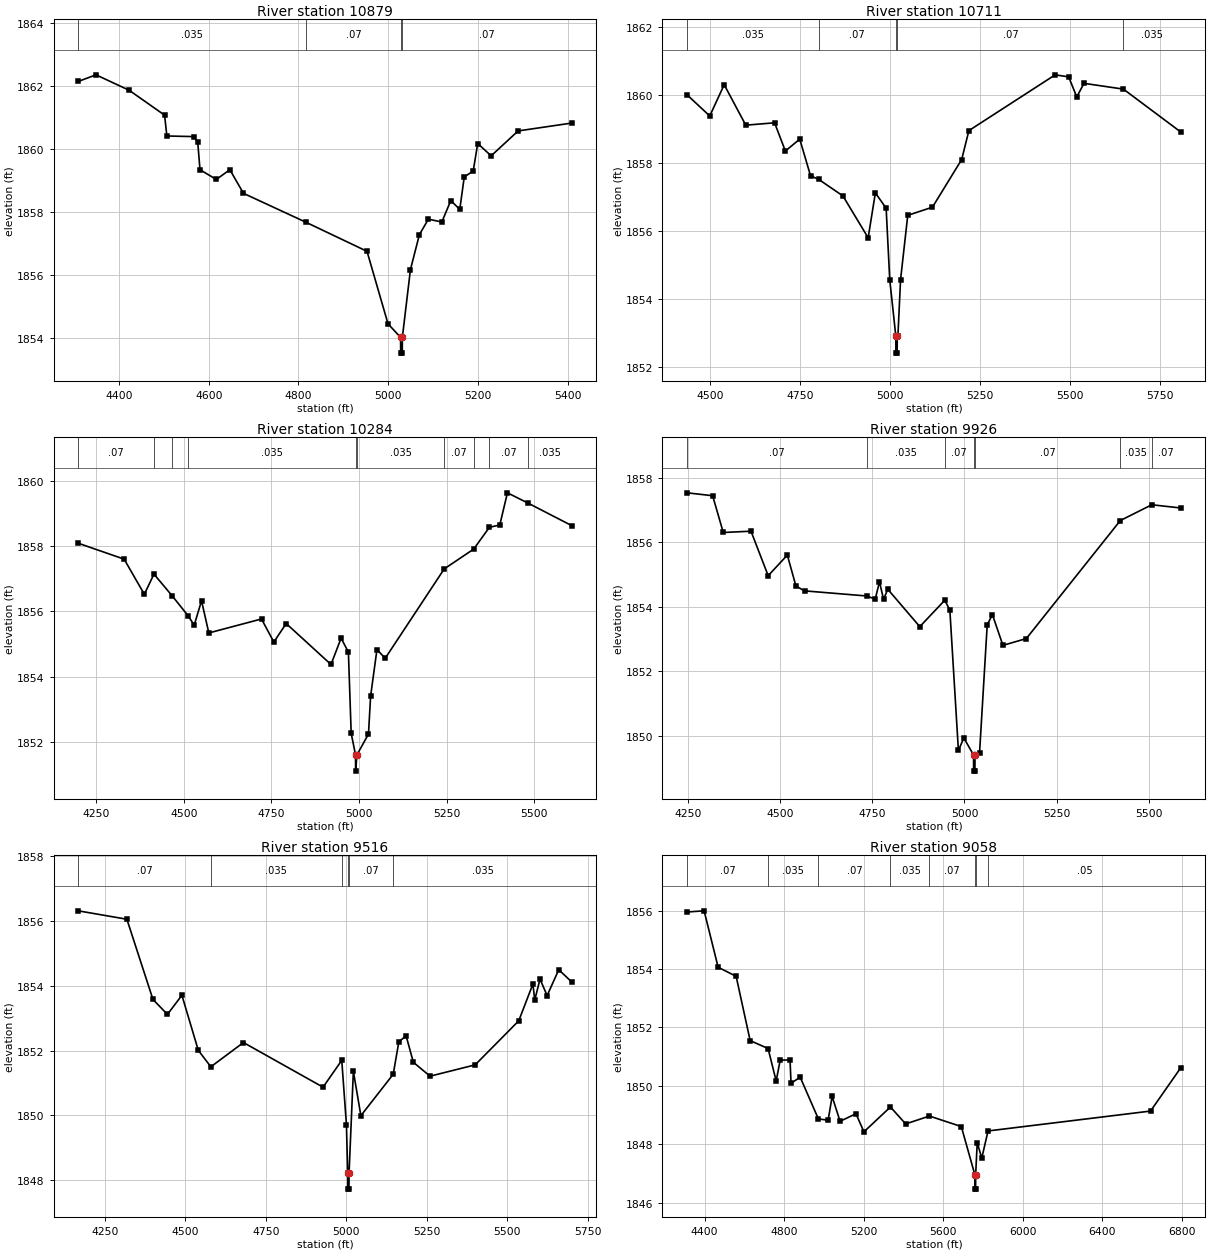
Type RM Length L Ch R = 1,10879,168,168,168
BEGIN DESCRIPTION:
Elm 01 12 10953.79
END DESCRIPTION:
XS GIS Cut Line= 3
      1560119.71      6803998.01      1560758.20      6803914.66
      1561214.73      6803921.91
#Sta/Elev= 30
  4309.0 1862.13  4348.7 1862.34  4422.6 1861.85  4501.6 1861.06  4506.6 1860.40
  4566.5 1860.38  4575.5 1860.20  4580.5 1859.33  4616.9 1859.02  4647.1 1859.33
  4677.4 1858.58  4817.1 1857.66  4952.9 1856.74  4999.7 1854.44  5027.7 1854.01
  5028.0 1853.51  5031.5 1853.51  5031.7 1854.01  5049.7 1856.16  5069.7 1857.27
  5089.7 1857.76  5119.7 1857.67  5139.7 1858.35  5159.7 1858.07  5169.7 1859.10
  5189.7 1859.29  5199.7 1860.16  5229.7 1859.77  5289.8 1860.56  5409.5 1860.81
#Mann=4,-1,0
  4309.0   0.035       0  4817.1    0.07       0  5027.7    0.07       0
  5031.7    0.07       0
Bank Sta=5027.7,5031.7
Exp/Cntr=0.3,0.1

Type RM Length L Ch R = 1,10711,427,427,427
BEGIN DESCRIPTION:
Elm 01 12 10693.07
END DESCRIPTION:
XS GIS Cut Line= 3
      1560242.15      6804084.77      1560827.63      6804055.64
      1561614.05      6804034.81
#Sta/Elev= 30
  4435.7 1860.01  4498.6 1859.39  4538.7 1860.31  4598.8 1859.12  4678.9 1859.19
  4708.9 1858.36  4748.9 1858.71  4779.0 1857.63  4801.2 1857.53  4869.0 1857.04
  4939.2 1855.81  4959.2 1857.13  4989.2 1856.68  4999.2 1854.58  5016.1 1852.92
  5016.3 1852.42  5019.8 1852.42  5020.1 1852.92  5021.9 1852.92  5029.3 1854.58
  5049.3 1856.47  5118.0 1856.71  5199.3 1858.11  5219.3 1858.96  5459.4 1860.60
  5496.9 1860.54  5519.4 1859.95  5539.5 1860.35  5649.1 1860.18  5808.6 1858.92
#Mann=5,-1,0
  4435.7   0.035       0  4801.2    0.07       0  5016.1    0.07       0
  5020.1    0.07       0  5649.1   0.035       0
Bank Sta=5016.1,5020.1
Exp/Cntr=0.3,0.1

Type RM Length L Ch R = 1,10284,358,358,358
BEGIN DESCRIPTION:
Elm 01 12 10284.26
END DESCRIPTION:
XS GIS Cut Line= 3
      1560426.62      6804894.16      1561072.42      6804373.35
      1561603.66      6804144.19
#Sta/Elev= 30
  4198.6 1858.10  4329.6 1857.61  4387.2 1856.53  4414.7 1857.15  4467.5 1856.47
  4512.0 1855.87  4529.5 1855.58  4550.4 1856.33  4571.2 1855.34  4721.5 1855.77
  4756.7 1855.06  4791.9 1855.63  4919.8 1854.37  4948.6 1855.18  4969.4 1854.75
  4977.4 1852.25  4989.8 1851.59  4990.0 1851.09  4993.8 1851.59  5026.7 1852.23
  5032.8 1853.40  5050.9 1854.83  5074.4 1854.56  5242.8 1857.31  5327.0 1857.92
  5371.7 1858.59  5401.3 1858.66  5423.1 1859.65  5480.8 1859.34  5606.8 1858.64
#Mann=10,-1,0
  4198.6    0.07       0  4414.7   0.035       0  4467.5    0.07       0
  4512.0   0.035       0  4989.8   0.035       0  4993.8   0.035       0
  5242.8    0.07       0  5327.0   0.035       0  5371.7    0.07       0
  5480.8   0.035       0
Bank Sta=4989.8,4993.8
Exp/Cntr=0.3,0.1

Type RM Length L Ch R = 1,9926,410,410,410
BEGIN DESCRIPTION:
Elm 01 12 9925.77
END DESCRIPTION:
XS GIS Cut Line= 3
      1560577.68      6804951.46      1561259.92      6804649.39
      1561697.40      6804248.37
#Sta/Elev= 30
  4247.3 1857.54  4316.5 1857.45  4345.3 1856.31  4420.6 1856.35  4467.2 1854.97
  4519.2 1855.61  4542.5 1854.65  4565.8 1854.50  4736.1 1854.34  4757.6 1854.24
  4769.3 1854.78  4780.3 1854.24  4791.8 1854.55  4878.7 1853.39  4946.6 1854.21
  4960.3 1853.90  4983.5 1849.55  4998.2 1849.94  5024.6 1849.41  5024.8 1848.91
  5028.3 1848.91  5028.6 1849.41  5040.8 1849.46  5061.7 1853.45  5075.9 1853.76
  5104.3 1852.81  5167.8 1853.02  5422.9 1856.68  5508.3 1857.17  5586.9 1857.07
#Mann=7,-1,0
  4247.3    0.07       0  4736.1   0.035       0  4946.6    0.07       0
  5024.6    0.07       0  5028.6    0.07       0  5422.9   0.035       0
  5508.3    0.07       0
Bank Sta=5024.6,5028.6
Exp/Cntr=0.3,0.1

Type RM Length L Ch R = 1,9516,458,458,458
BEGIN DESCRIPTION:
Elm 01 12 9516.29
END DESCRIPTION:
XS GIS Cut Line= 3
      1560848.45      6805253.57      1561608.88      6804862.94
      1561924.07      6804262.08
#Sta/Elev= 30
  4167.4 1856.32  4318.6 1856.06  4399.6 1853.58  4444.6 1853.12  4489.5 1853.71
  4540.4 1852.01  4579.4 1851.50  4680.7 1852.25  4928.0 1850.87  4986.1 1851.70
  5000.7 1849.70  5004.5 1848.22  5004.8 1847.72  5008.5 1847.72  5008.8 1848.22
  5022.2 1851.36  5045.5 1849.99  5146.0 1851.27  5163.4 1852.27  5186.0 1852.46
  5208.5 1851.64  5260.4 1851.21  5400.5 1851.56  5535.9 1852.92  5580.0 1854.06
  5585.6 1853.56  5602.0 1854.21  5624.1 1853.70  5660.2 1854.50  5700.8 1854.12
#Mann=6,-1,0
  4167.4    0.07       0  4579.4   0.035       0  4986.1    0.07       0
  5004.5    0.07       0  5008.8    0.07       0  5146.0   0.035       0
Bank Sta=5004.5,5008.8
Exp/Cntr=0.3,0.1

Type RM Length L Ch R = 1,9058,393,393,393
BEGIN DESCRIPTION:
Elm 01 12 9059.94
END DESCRIPTION:
XS GIS Cut Line= 4
      1560890.15      6805383.77      1561556.80      6805305.64
      1562367.86      6805291.55      1563366.66      6805223.59
#Sta/Elev= 30
  4312.4 1855.95  4397.8 1855.99  4468.3 1854.06  4558.9 1853.75  4629.4 1851.55
  4719.6 1851.28  4760.3 1850.17  4780.4 1850.88  4830.1 1850.89  4835.1 1850.09
  4881.1 1850.30  4972.8 1848.87  5021.8 1848.83  5041.8 1849.64  5081.8 1848.79
  5161.8 1849.05  5201.8 1848.43  5335.3 1849.28  5411.9 1848.70  5531.5 1848.97
  5691.9 1848.61  5759.7 1846.97  5760.0 1846.47  5763.8 1846.47  5764.1 1846.97
  5771.9 1848.06  5794.8 1847.53  5826.3 1848.46  6643.9 1849.14  6795.9 1850.62
#Mann=8,-1,0
  4312.4    0.07       0  4719.6   0.035       0  4972.8    0.07       0
  5335.3   0.035       0  5531.5    0.07       0  5759.7    0.07       0
  5764.1    0.07       0  5826.3    0.05       0
Bank Sta=5759.7,5764.1
Exp/Cntr=0.3,0.1

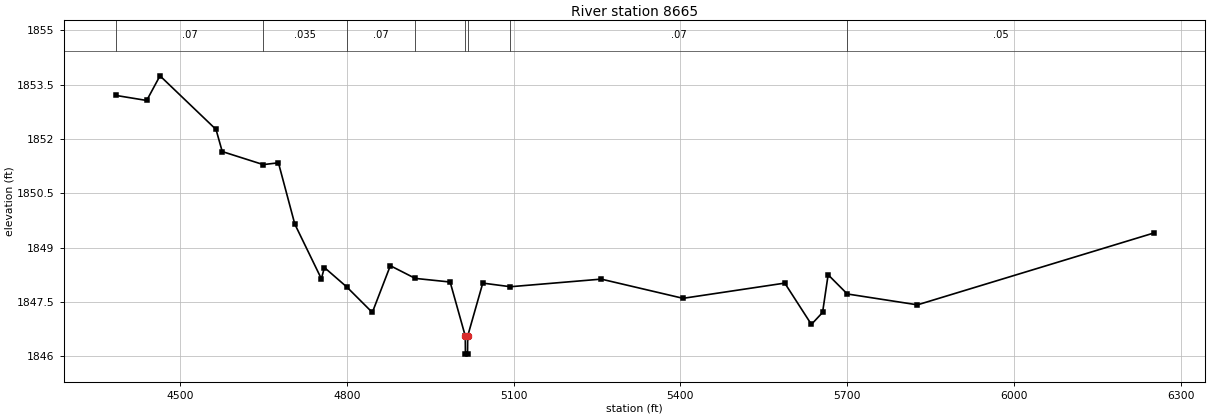
Type RM Length L Ch R = 1,8665,304,304,304
BEGIN DESCRIPTION:
Elm 01 12 8628.83
END DESCRIPTION:
XS GIS Cut Line= 3
      1561148.14      6805884.12      1562050.00      6805512.41
      1562937.92      6805593.81
#Sta/Elev= 30
  4384.0 1853.20  4439.8 1853.06  4463.7 1853.74  4564.5 1852.26  4575.7 1851.65
  4649.5 1851.29  4676.8 1851.34  4706.2 1849.65  4754.0 1848.14  4759.5 1848.45
  4800.0 1847.91  4845.7 1847.21  4878.1 1848.50  4922.9 1848.15  4985.7 1848.05
  5012.9 1846.56  5013.2 1846.06  5017.0 1846.06  5017.3 1846.56  5044.4 1848.02
  5094.2 1847.92  5257.5 1848.13  5404.7 1847.60  5587.7 1848.02  5635.6 1846.88
  5655.7 1847.21  5665.7 1848.25  5700.2 1847.72  5826.4 1847.42  6251.1 1849.40
#Mann=8,-1,0
  4384.0    0.07       0  4649.5   0.035       0  4800.0    0.07       0
  4922.9   0.035       0  5012.9   0.035       0  5017.3   0.035       0
  5094.2    0.07       0  5700.2    0.05       0
Bank Sta=5012.9,5017.3
Exp/Cntr=0.3,0.1