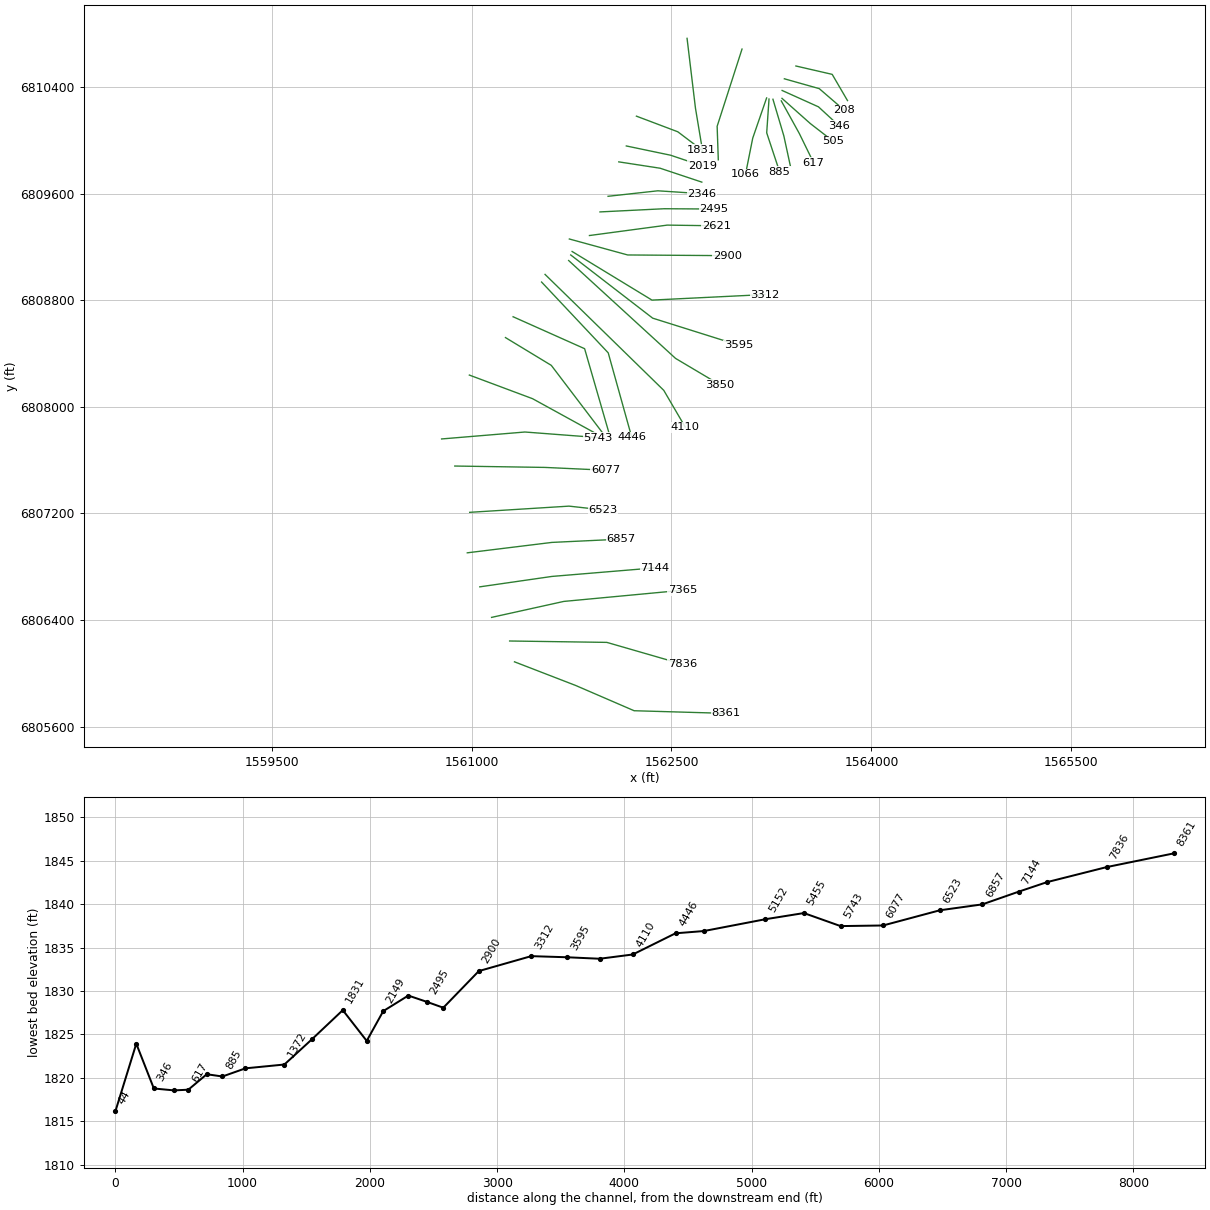
HEC-RAS study Elm 01 12.prj: Elm 01 12 Base Level Engineering

--- Elm 01 12.g01 (geometry) --- (continued)

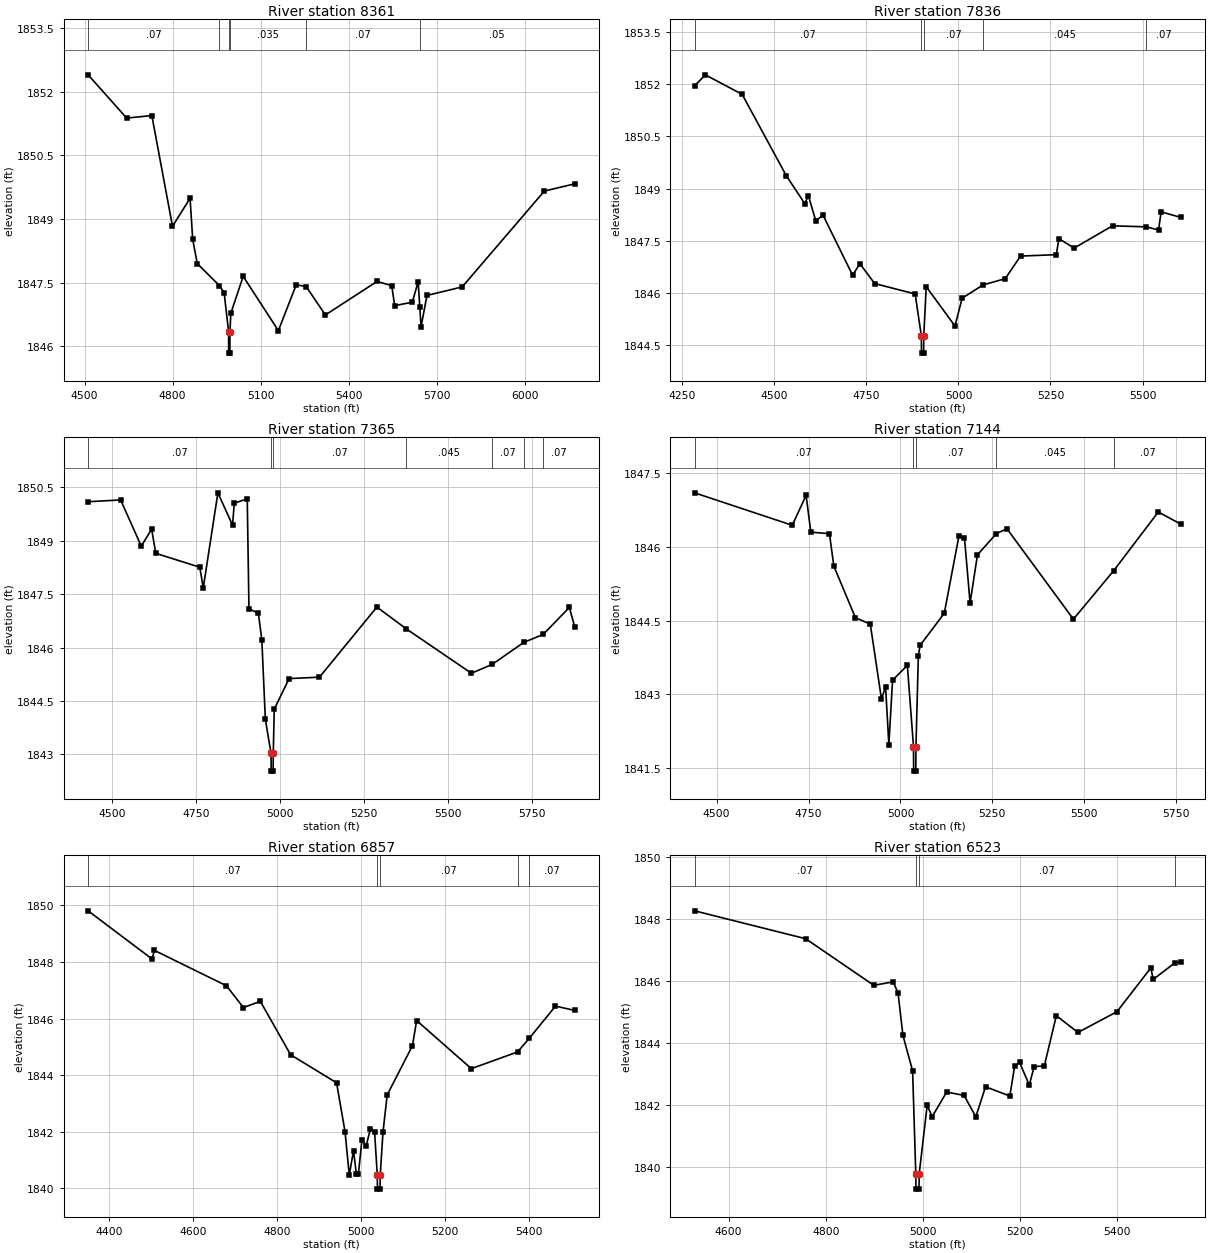
Type RM Length L Ch R = 1,8361,525,525,525
BEGIN DESCRIPTION:
Elm 01 12 8361.3
END DESCRIPTION:
XS GIS Cut Line= 4
      1561322.43      6806086.89      1561780.76      6805909.81
      1562219.89      6805720.03      1562908.16      6805700.19
#Sta/Elev= 30
  4512.2 1852.40  4643.6 1851.38  4729.4 1851.44  4799.8 1848.83  4859.7 1849.49
  4868.7 1848.52  4884.3 1847.95  4960.0 1847.43  4975.9 1847.26  4991.1 1846.34
  4991.4 1845.84  4995.3 1845.84  4995.6 1846.34  4998.7 1846.78  5040.7 1847.65
  5160.7 1846.37  5221.5 1847.45  5255.4 1847.41  5320.9 1846.74  5497.1 1847.53
  5547.1 1847.43  5557.1 1846.96  5617.1 1847.04  5637.1 1847.52  5642.7 1846.93
  5647.1 1846.46  5667.1 1847.20  5787.2 1847.40  6067.3 1849.66  6170.5 1849.83
#Mann=6,-1,0
  4512.2    0.07       0  4960.0   0.035       0  4991.1   0.035       0
  4995.6   0.035       0  5255.4    0.07       0  5642.7    0.05       0
Bank Sta=4991.1,4995.6
Exp/Cntr=0.3,0.1

Type RM Length L Ch R = 1,7836,471,471,471
BEGIN DESCRIPTION:
Elm 01 12 7836.15
END DESCRIPTION:
XS GIS Cut Line= 3
      1561285.93      6806243.14      1562015.13      6806232.73
      1562583.92      6806068.49
#Sta/Elev= 30
  4283.4 1851.95  4312.5 1852.27  4412.5 1851.71  4532.5 1849.37  4582.5 1848.57
  4592.5 1848.79  4612.5 1848.08  4632.5 1848.23  4712.5 1846.51  4732.5 1846.84
  4772.5 1846.27  4882.5 1845.97  4899.2 1844.77  4899.7 1844.27  4905.4 1844.27
  4905.9 1844.77  4912.5 1846.18  4990.6 1845.05  5010.1 1845.85  5066.7 1846.23
  5127.0 1846.41  5168.7 1847.06  5265.8 1847.10  5272.8 1847.56  5314.4 1847.29
  5418.5 1847.93  5509.8 1847.90  5543.4 1847.81  5550.5 1848.33  5604.7 1848.17
#Mann=5,-1,0
  4283.4    0.07       0  4899.2    0.07       0  4905.9    0.07       0
  5066.7   0.045       0  5509.8    0.07       0
Bank Sta=4899.2,4905.9
Exp/Cntr=0.3,0.1

Type RM Length L Ch R = 1,7365,221,221,221
BEGIN DESCRIPTION:
Elm 01 12 7366.97
END DESCRIPTION:
XS GIS Cut Line= 3
      1561150.54      6806420.23      1561692.22      6806540.02
      1562580.53      6806623.56
#Sta/Elev= 30
  4429.3 1850.10  4526.0 1850.15  4587.5 1848.85  4618.2 1849.33  4630.5 1848.65
  4761.4 1848.26  4771.8 1847.68  4815.3 1850.35  4858.9 1849.44  4864.0 1850.06
  4902.6 1850.18  4907.7 1847.09  4935.7 1846.97  4946.0 1846.21  4956.4 1843.99
  4973.3 1843.03  4973.8 1842.53  4979.5 1842.53  4980.0 1843.03  4982.9 1844.27
  5027.0 1845.13  5117.4 1845.17  5288.2 1847.14  5375.2 1846.53  5569.4 1845.28
  5631.2 1845.53  5725.6 1846.15  5782.7 1846.37  5860.7 1847.13  5876.3 1846.59
#Mann=7,-1,0
  4429.3    0.07       0  4973.3    0.07       0  4980.0    0.07       0
  5375.2   0.045       0  5631.2    0.07       0  5725.6   0.045       0
  5782.7    0.07       0
Bank Sta=4973.3,4980
Exp/Cntr=0.3,0.1

Type RM Length L Ch R = 1,7144,287,287,287
BEGIN DESCRIPTION:
Elm 01 12 7147.58
END DESCRIPTION:
XS GIS Cut Line= 3
      1561061.99      6806649.39      1561603.67      6806727.52
      1562376.91      6806791.91
#Sta/Elev= 30
  4440.1 1847.10  4705.8 1846.44  4743.4 1847.05  4756.3 1846.30  4806.9 1846.27
  4818.8 1845.61  4877.6 1844.56  4918.0 1844.43  4948.3 1842.91  4959.6 1843.15
  4968.5 1841.98  4978.6 1843.29  5018.8 1843.59  5035.5 1841.94  5036.0 1841.44
  5041.7 1841.44  5042.2 1841.94  5048.7 1843.79  5053.7 1844.00  5119.2 1844.65
  5159.3 1846.23  5174.1 1846.19  5189.4 1844.86  5209.5 1845.84  5260.9 1846.27
  5289.6 1846.37  5470.4 1844.53  5580.4 1845.52  5701.2 1846.71  5763.3 1846.46
#Mann=5,-1,0
  4440.1    0.07       0  5035.5    0.07       0  5042.2    0.07       0
  5260.9   0.045       0  5580.4    0.07       0
Bank Sta=5035.5,5042.2
Exp/Cntr=0.3,0.1

Type RM Length L Ch R = 1,6857,334,334,334
BEGIN DESCRIPTION:
Elm 01 12 6859.27
END DESCRIPTION:
XS GIS Cut Line= 3
      1560968.26      6806904.60      1561603.67      6806982.73
      1562120.50      6807007.09
#Sta/Elev= 30
  4350.2 1849.81  4502.0 1848.11  4508.1 1848.41  4679.4 1847.16  4719.7 1846.39
  4760.0 1846.61  4832.1 1844.72  4941.4 1843.73  4961.5 1842.00  4971.6 1840.47
  4981.7 1841.33  4988.5 1840.50  4993.3 1840.50  5001.7 1841.71  5011.7 1841.49
  5021.8 1842.10  5031.8 1842.00  5038.2 1840.47  5038.7 1839.97  5044.8 1839.97
  5045.3 1840.47  5051.8 1841.98  5061.8 1843.30  5121.9 1845.04  5131.9 1845.93
  5262.0 1844.23  5372.0 1844.82  5400.4 1845.31  5462.2 1846.44  5507.8 1846.29
#Mann=5,-1,0
  4350.2    0.07       0  5038.2    0.07       0  5045.3    0.07       0
  5372.0   0.045       0  5400.4    0.07       0
Bank Sta=5038.2,5045.3
Exp/Cntr=0.3,0.1

Type RM Length L Ch R = 1,6523,446,446,446
BEGIN DESCRIPTION:
Elm 01 12 6503.63
END DESCRIPTION:
XS GIS Cut Line= 3
      1560986.35      6807208.30      1561731.48      6807254.84
      1561986.34      6807226.60
#Sta/Elev= 30
  4529.7 1848.26  4758.8 1847.36  4899.1 1845.86  4939.1 1845.97  4949.2 1845.61
  4959.2 1844.25  4979.2 1843.10  4985.7 1839.79  4986.2 1839.29  4992.3 1839.29
  4992.8 1839.79  5009.3 1842.00  5019.3 1841.62  5049.4 1842.42  5085.4 1842.31
  5109.5 1841.62  5129.5 1842.59  5179.6 1842.29  5189.6 1843.26  5199.7 1843.38
  5219.7 1842.64  5229.7 1843.24  5250.7 1843.26  5275.5 1844.88  5320.1 1844.34
  5400.6 1845.01  5470.3 1846.42  5475.3 1846.05  5519.6 1846.58  5532.7 1846.62
#Mann=4,-1,0
  4529.7    0.07       0  4985.7    0.07       0  4992.8    0.07       0
  5519.6   0.045       0
Bank Sta=4985.7,4992.8
Exp/Cntr=0.3,0.1

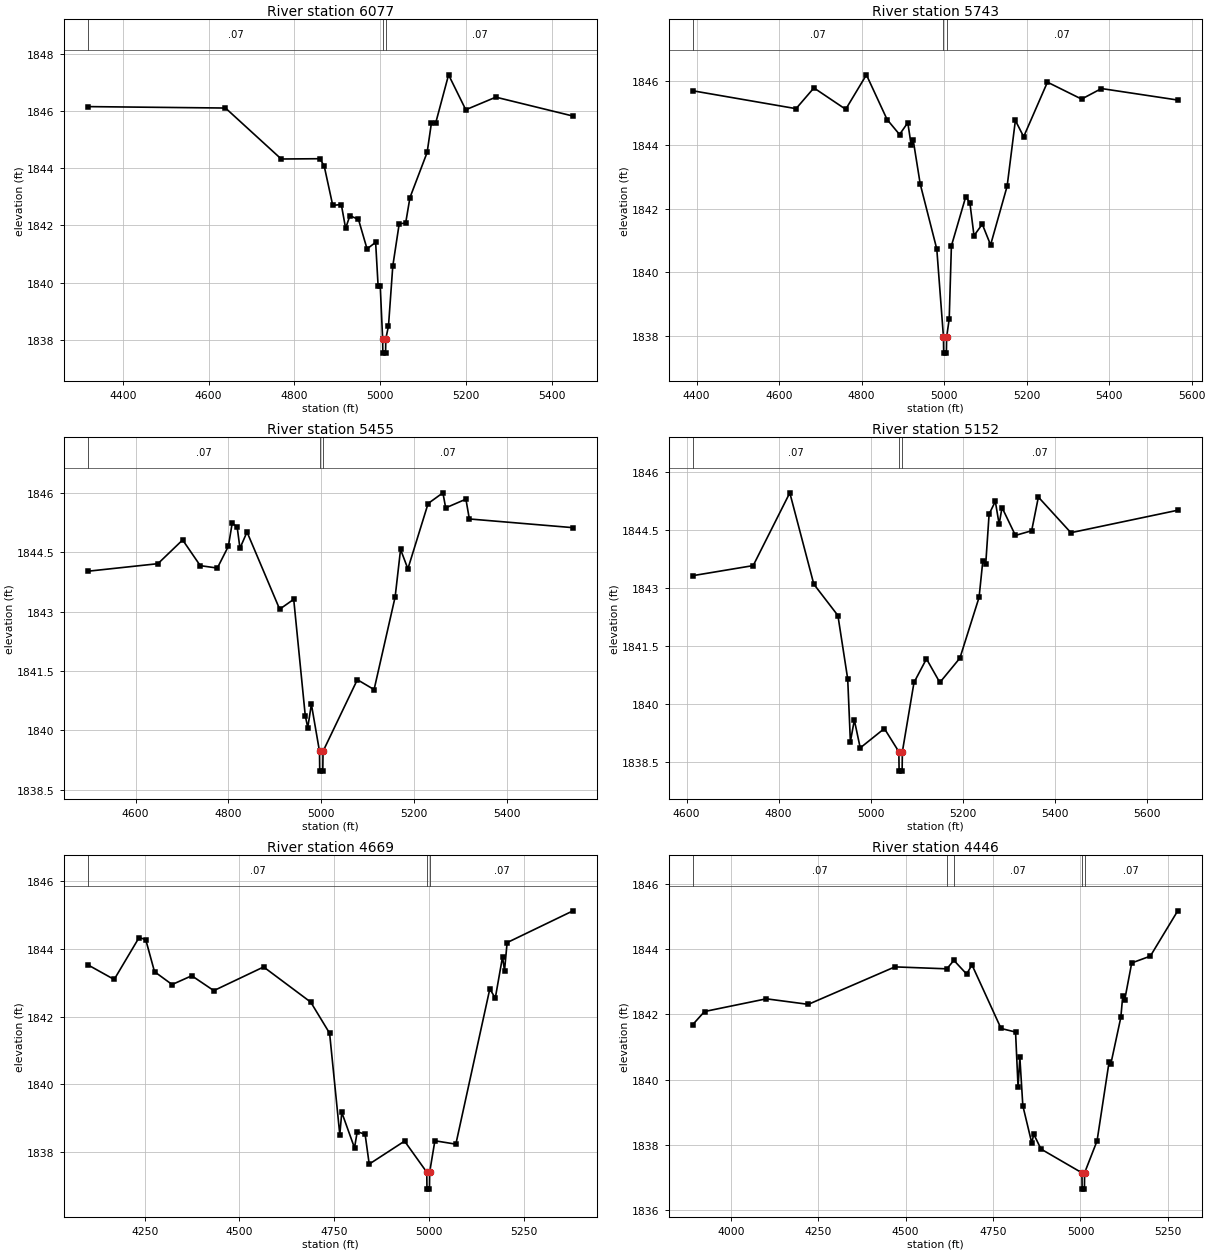
Type RM Length L Ch R = 1,6077,334,334,334
BEGIN DESCRIPTION:
Elm 01 12 6076.6
END DESCRIPTION:
XS GIS Cut Line= 3
      1560874.51      6807555.64      1561551.59      6807545.23
      1562004.76      6807524.39
#Sta/Elev= 30
  4318.7 1846.15  4639.2 1846.10  4769.2 1844.32  4859.2 1844.33  4869.3 1844.08
  4889.3 1842.70  4909.3 1842.73  4919.3 1841.90  4929.3 1842.34  4949.3 1842.21
  4969.3 1841.18  4989.3 1841.41  4995.1 1839.88  5000.1 1839.88  5005.6 1838.04
  5006.1 1837.54  5012.5 1837.54  5013.0 1838.04  5019.3 1838.49  5029.3 1840.58
  5044.3 1842.06  5059.3 1842.08  5069.3 1842.97  5109.4 1844.55  5119.4 1845.58
  5129.4 1845.58  5159.4 1847.26  5199.5 1846.04  5269.6 1846.48  5449.5 1845.82
#Mann=3,-1,0
  4318.7    0.07       0  5005.6    0.07       0  5013.0    0.07       0
Bank Sta=5005.6,5013
Exp/Cntr=0.3,0.1

Type RM Length L Ch R = 1,5743,288,288,288
BEGIN DESCRIPTION:
Elm 01 12 5743.13
END DESCRIPTION:
XS GIS Cut Line= 3
      1560775.58      6807758.77      1561400.55      6807810.85
      1561947.43      6807769.19
#Sta/Elev= 30
  4390.7 1845.69  4641.0 1845.13  4684.3 1845.78  4761.4 1845.11  4811.6 1846.19
  4861.7 1844.79  4891.9 1844.32  4911.9 1844.69  4920.1 1843.99  4925.1 1844.14
  4942.0 1842.77  4982.2 1840.73  4998.4 1837.97  4998.9 1837.47  5005.5 1837.47
  5006.0 1837.97  5012.3 1838.54  5017.6 1840.83  5052.4 1842.37  5062.4 1842.18
  5072.4 1841.15  5092.5 1841.51  5112.6 1840.86  5152.7 1842.70  5172.7 1844.76
  5192.8 1844.25  5250.4 1845.96  5333.2 1845.43  5381.4 1845.76  5566.3 1845.40
#Mann=3,-1,0
  4390.7    0.07       0  4998.4    0.07       0  5006.0    0.07       0
Bank Sta=4998.4,5006
Exp/Cntr=0.3,0.1

Type RM Length L Ch R = 1,5455,303,303,303
BEGIN DESCRIPTION:
Elm 01 12 5454.96
END DESCRIPTION:
XS GIS Cut Line= 3
      1560983.87      6808237.94      1561457.84      6808060.85
      1561930.87      6807800.95
#Sta/Elev= 30
  4497.3 1844.02  4648.0 1844.21  4701.3 1844.81  4739.3 1844.16  4776.1 1844.10
  4799.9 1844.65  4808.1 1845.23  4818.8 1845.14  4824.9 1844.60  4840.1 1845.01
  4910.5 1843.06  4940.8 1843.31  4965.7 1840.37  4971.1 1840.07  4978.9 1840.66
  4996.4 1839.47  4996.9 1838.97  5003.5 1838.97  5004.0 1839.47  5078.0 1841.28
  5114.1 1841.03  5159.5 1843.37  5171.2 1844.57  5187.0 1844.08  5230.6 1845.73
  5262.5 1846.00  5268.5 1845.62  5312.1 1845.84  5319.5 1845.34  5543.0 1845.12
#Mann=3,-1,0
  4497.3    0.07       0  4996.4    0.07       0  5004.0    0.07       0
Bank Sta=4996.4,5004
Exp/Cntr=0.3,0.1

Type RM Length L Ch R = 1,5152,483,483,483
BEGIN DESCRIPTION:
Elm 01 12 5152.12
END DESCRIPTION:
XS GIS Cut Line= 3
      1561254.68      6808519.21      1561598.47      6808310.85
      1561993.16      6807791.51
#Sta/Elev= 30
  4613.3 1843.31  4744.6 1843.57  4824.2 1845.45  4876.4 1843.09  4928.8 1842.28
  4950.1 1840.64  4955.9 1839.02  4964.5 1839.58  4977.3 1838.86  5029.8 1839.36
  5061.3 1838.76  5061.8 1838.26  5068.4 1838.26  5068.9 1838.76  5094.2 1840.55
  5121.3 1841.16  5150.4 1840.55  5194.0 1841.18  5235.7 1842.75  5243.9 1843.70
  5250.2 1843.62  5257.5 1844.90  5271.0 1845.23  5279.3 1844.64  5285.6 1845.07
  5314.7 1844.35  5350.0 1844.47  5364.6 1845.34  5435.3 1844.42  5667.6 1845.00
#Mann=3,-1,0
  4613.3    0.07       0  5061.3    0.07       0  5068.9    0.07       0
Bank Sta=5061.3,5068.9
Exp/Cntr=0.3,0.1

Type RM Length L Ch R = 1,4669,223,223,223
BEGIN DESCRIPTION:
Elm 01 12 4668.5
END DESCRIPTION:
XS GIS Cut Line= 3
      1561311.96      6808675.46      1561848.47      6808435.85
      1562040.64      6807771.05
#Sta/Elev= 30
  4100.6 1843.53  4169.6 1843.10  4235.3 1844.34  4252.8 1844.28  4276.0 1843.33
  4322.4 1842.95  4374.3 1843.21  4432.5 1842.77  4563.9 1843.47  4688.2 1842.43
  4738.0 1841.51  4764.9 1838.51  4770.1 1839.17  4803.7 1838.12  4810.9 1838.60
  4831.7 1838.52  4842.5 1837.64  4935.8 1838.32  4994.4 1837.40  4994.9 1836.90
  5001.5 1836.90  5002.0 1837.40  5015.8 1838.33  5071.1 1838.23  5160.7 1842.82
  5175.2 1842.55  5194.3 1843.77  5199.5 1843.36  5206.4 1844.19  5380.2 1845.13
#Mann=3,-1,0
  4100.6    0.07       0  4994.4    0.07       0  5002.0    0.07       0
Bank Sta=4994.4,5002
Exp/Cntr=0.3,0.1

Type RM Length L Ch R = 1,4446,336,336,336
BEGIN DESCRIPTION:
Elm 01 12 4446.08
END DESCRIPTION:
XS GIS Cut Line= 3
      1561525.58      6808935.82      1562025.55      6808404.60
      1562202.09      6807771.13
#Sta/Elev= 30
  3891.1 1841.69  3924.6 1842.09  4101.4 1842.48  4221.5 1842.31  4469.2 1843.46
  4617.7 1843.40  4637.9 1843.66  4674.3 1843.24  4689.7 1843.52  4772.8 1841.57
  4814.3 1841.46  4821.5 1839.77  4826.6 1840.68  4835.1 1839.20  4860.8 1838.05
  4866.2 1838.33  4887.0 1837.87  5004.2 1837.14  5004.7 1836.64  5011.3 1836.64
  5011.8 1837.14  5047.4 1838.12  5081.6 1840.53  5086.8 1840.48  5115.4 1841.91
  5121.0 1842.58  5126.2 1842.43  5146.5 1843.58  5199.8 1843.79  5278.2 1845.18
#Mann=5,-1,0
  3891.1    0.07       0  4617.7   0.035       0  4637.9    0.07       0
  5004.2    0.07       0  5011.8    0.07       0
Bank Sta=5004.2,5011.8
Exp/Cntr=0.3,0.1

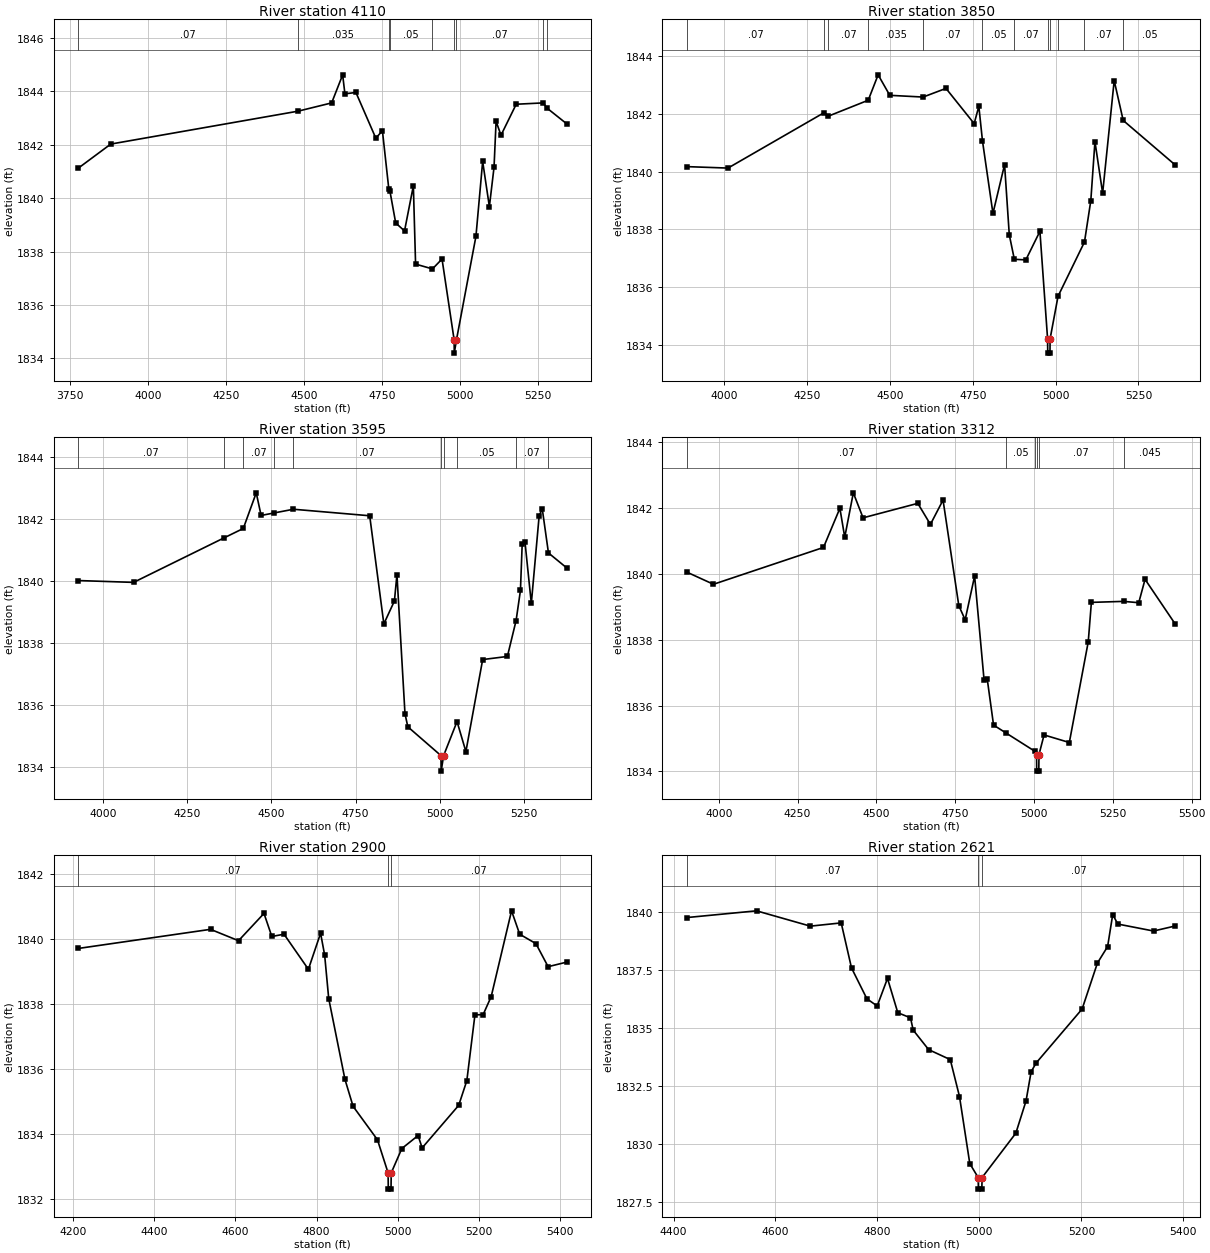
Type RM Length L Ch R = 1,4110,260,260,260
BEGIN DESCRIPTION:
Elm 01 12 4109.89
END DESCRIPTION:
XS GIS Cut Line= 3
      1561551.59      6808993.15      1562442.22      6808123.35
      1562603.68      6807847.30
#Sta/Elev= 30
  3776.3 1841.11  3881.3 1842.02  4480.8 1843.25  4588.6 1843.56  4623.8 1844.61
  4631.0 1843.90  4666.3 1843.95  4730.0 1842.24  4751.1 1842.52  4771.6 1840.34
  4774.9 1840.28  4793.6 1839.07  4821.9 1838.77  4850.2 1840.46  4857.3 1837.53
  4911.3 1837.35  4942.0 1837.72  4980.7 1834.70  4981.2 1834.20  4988.3 1834.70
  5050.6 1838.57  5072.1 1841.37  5093.6 1839.68  5108.5 1841.15  5115.1 1842.87
  5130.8 1842.35  5179.5 1843.51  5266.2 1843.56  5277.6 1843.37  5341.0 1842.78
#Mann=9,-1,0
  3776.3    0.07       0  4480.8   0.035       0  4771.6    0.07       0
  4774.9    0.05       0  4911.3    0.07       0  4980.7    0.07       0
  4988.3    0.07       0  5266.2    0.05       0  5277.6    0.07       0
Bank Sta=4980.7,4988.3
Exp/Cntr=0.3,0.1

Type RM Length L Ch R = 1,3850,255,255,255
BEGIN DESCRIPTION:
Elm 01 12 3849.54
END DESCRIPTION:
XS GIS Cut Line= 3
      1561728.70      6809097.29      1562530.76      6808362.94
      1562864.07      6808165.03
#Sta/Elev= 30
  3886.8 1840.17  4011.1 1840.12  4301.3 1842.04  4314.3 1841.92  4434.4 1842.47
  4464.3 1843.35  4499.5 1842.64  4600.0 1842.58  4669.1 1842.88  4754.2 1841.66
  4768.3 1842.26  4779.3 1841.06  4810.9 1838.55  4846.0 1840.24  4860.2 1837.81
  4875.5 1836.96  4910.2 1836.94  4952.7 1837.93  4975.8 1834.21  4976.3 1833.71
  4983.0 1833.71  4983.5 1834.21  5007.4 1835.68  5087.2 1837.56  5106.3 1838.99
  5118.8 1841.04  5142.0 1839.25  5176.9 1843.15  5204.1 1841.77  5361.9 1840.22
#Mann=12,-1,0
  3886.8    0.07       0  4301.3   0.035       0  4314.3    0.07       0
  4434.4   0.035       0  4600.0    0.07       0  4779.3    0.05       0
  4875.5    0.07       0  4975.8    0.07       0  4983.5    0.07       0
  5007.4    0.05       0  5087.2    0.07       0  5204.1    0.05       0
Bank Sta=4975.8,4983.5
Exp/Cntr=0.3,0.1

Type RM Length L Ch R = 1,3595,283,283,283
BEGIN DESCRIPTION:
Elm 01 12 3594.7
END DESCRIPTION:
XS GIS Cut Line= 3
      1561744.27      6809139.00      1562358.88      6808665.02
      1563002.93      6808462.45
#Sta/Elev= 30
  3925.4 1840.03  4090.5 1839.97  4359.9 1841.41  4416.4 1841.71  4454.8 1842.86
  4469.3 1842.13  4507.6 1842.21  4565.3 1842.33  4791.8 1842.12  4833.8 1838.63
  4865.2 1839.37  4872.7 1840.22  4896.6 1835.73  4905.1 1835.31  5003.6 1834.38
  5004.1 1833.88  5011.3 1834.38  5051.2 1835.48  5077.5 1834.51  5127.3 1837.48
  5200.7 1837.58  5226.6 1838.74  5239.5 1839.71  5244.7 1841.21  5253.1 1841.26
  5271.8 1839.29  5295.0 1842.11  5304.2 1842.35  5322.7 1840.92  5376.7 1840.44
#Mann=10,-1,0
  3925.4    0.07       0  4359.9   0.035       0  4416.4    0.07       0
  4507.6   0.035       0  4565.3    0.07       0  5003.6    0.07       0
  5011.3    0.07       0  5051.2    0.05       0  5226.6    0.07       0
  5322.7    0.05       0
Bank Sta=5003.6,5011.3
Exp/Cntr=0.3,0.1

Type RM Length L Ch R = 1,3312,412,412,412
BEGIN DESCRIPTION:
Elm 01 12 3312.28
END DESCRIPTION:
XS GIS Cut Line= 3
      1561754.70      6809165.03      1562353.67      6808800.44
      1563201.34      6808842.04
#Sta/Elev= 30
  3898.8 1840.06  3983.3 1839.69  4332.3 1840.81  4384.3 1842.00  4399.7 1841.12
  4426.9 1842.47  4457.8 1841.71  4631.4 1842.15  4671.4 1841.51  4711.5 1842.25
  4761.5 1839.04  4781.6 1838.61  4811.6 1839.94  4841.6 1836.78  4851.5 1836.82
  4871.7 1835.41  4911.1 1835.17  5003.3 1834.61  5008.0 1834.51  5008.5 1834.01
  5015.2 1834.01  5015.7 1834.51  5031.9 1835.11  5112.0 1834.88  5172.0 1837.94
  5182.0 1839.14  5284.1 1839.17  5332.2 1839.13  5352.2 1839.84  5448.7 1838.47
#Mann=6,-1,0
  3898.8    0.07       0  4911.1    0.05       0  5003.3    0.07       0
  5008.0    0.05       0  5015.7    0.07       0  5284.1   0.045       0
Bank Sta=5008,5015.7
Exp/Cntr=0.3,0.1

Type RM Length L Ch R = 1,2900,279,279,279
BEGIN DESCRIPTION:
Elm 01 12 2899.96
END DESCRIPTION:
XS GIS Cut Line= 3
      1561733.87      6809258.77      1562171.38      6809138.98
      1562920.65      6809133.77
#Sta/Elev= 30
  4212.5 1839.70  4538.8 1840.29  4607.7 1839.94  4670.4 1840.78  4689.7 1840.07
  4719.7 1840.14  4779.7 1839.06  4809.7 1840.17  4819.7 1839.50  4829.7 1838.16
  4869.7 1835.67  4889.7 1834.84  4949.7 1833.81  4975.9 1832.79  4976.4 1832.29
  4983.1 1832.29  4983.6 1832.79  5009.7 1833.54  5049.7 1833.94  5059.7 1833.56
  5149.7 1834.87  5169.7 1835.63  5189.7 1837.66  5209.7 1837.66  5229.7 1838.22
  5279.8 1840.86  5299.8 1840.14  5339.8 1839.85  5369.8 1839.14  5415.4 1839.28
#Mann=3,-1,0
  4212.5    0.07       0  4975.9    0.07       0  4983.6    0.07       0
Bank Sta=4975.9,4983.6
Exp/Cntr=0.3,0.1

Type RM Length L Ch R = 1,2621,126,126,126
BEGIN DESCRIPTION:
Elm 01 12 2620.87
END DESCRIPTION:
XS GIS Cut Line= 3
      1561884.88      6809284.81      1562468.26      6809362.94
      1562838.04      6809357.73
#Sta/Elev= 30
  4426.1 1839.77  4562.8 1840.06  4668.4 1839.40  4728.9 1839.54  4749.1 1837.60
  4779.3 1836.27  4799.5 1835.96  4819.7 1837.15  4839.9 1835.67  4864.8 1835.45
  4870.1 1834.92  4900.4 1834.08  4942.8 1833.65  4960.9 1832.06  4981.1 1829.17
  4997.5 1828.57  4998.0 1828.07  5004.7 1828.07  5005.2 1828.57  5071.4 1830.48
  5091.4 1831.87  5101.4 1833.13  5111.4 1833.51  5201.4 1835.83  5231.4 1837.81
  5251.4 1838.52  5261.4 1839.90  5271.4 1839.49  5341.5 1839.19  5384.5 1839.41
#Mann=3,-1,0
  4426.1    0.07       0  4997.5    0.07       0  5005.2    0.07       0
Bank Sta=4997.5,5005.2
Exp/Cntr=0.3,0.1

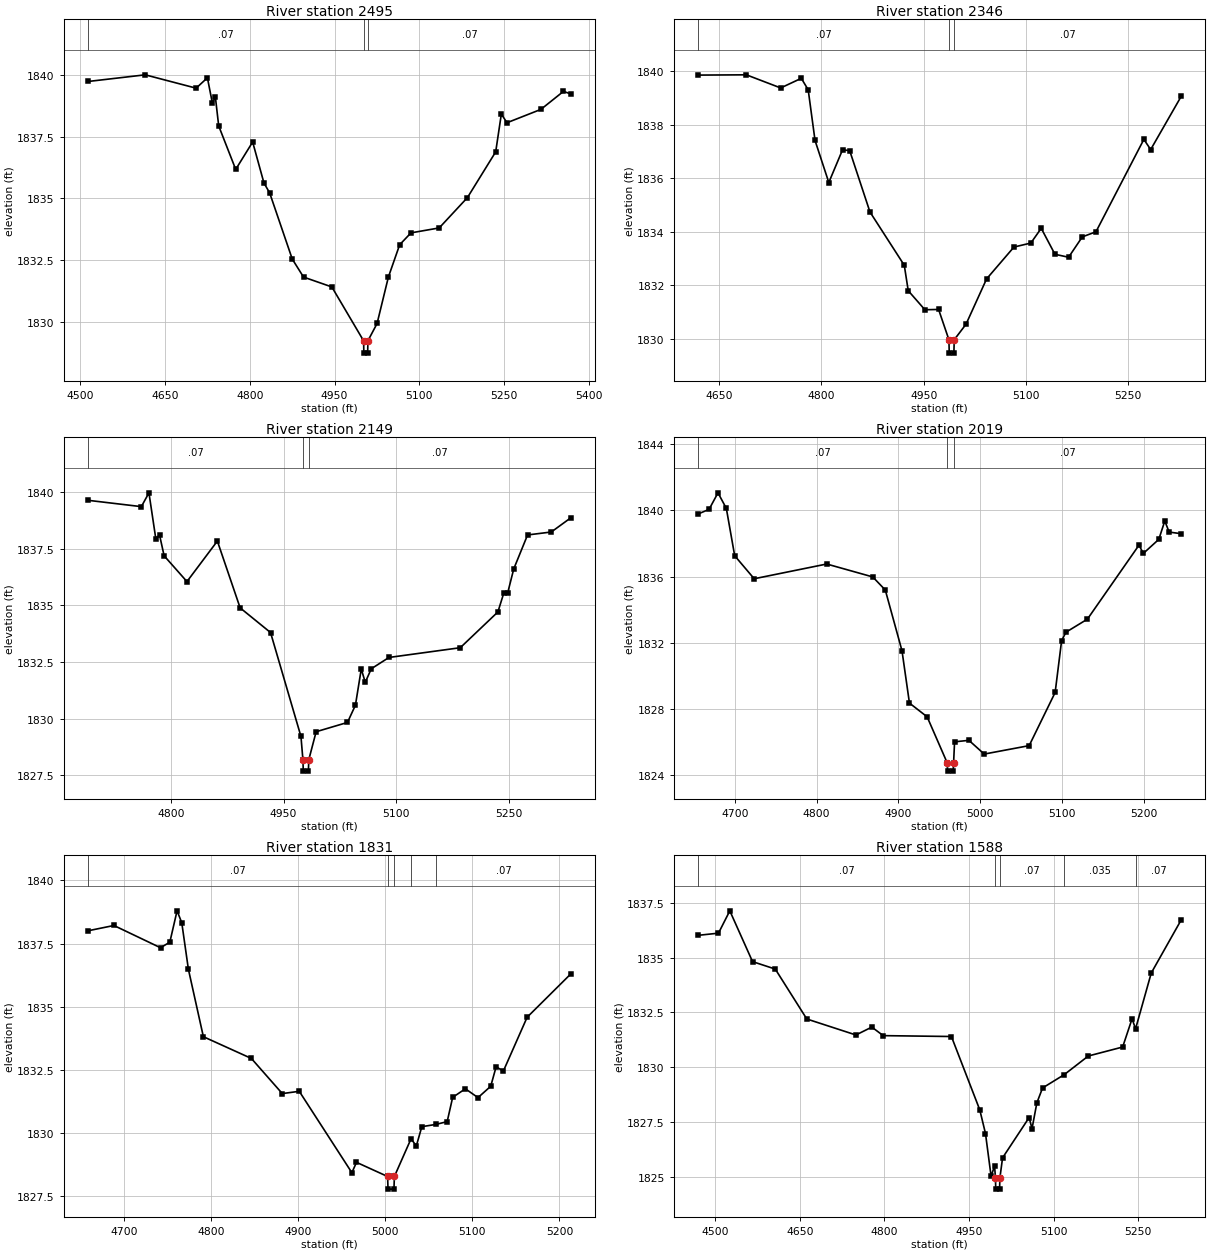
Type RM Length L Ch R = 1,2495,149,149,149
BEGIN DESCRIPTION:
Elm 01 12 2495.3
END DESCRIPTION:
XS GIS Cut Line= 3
      1561963.74      6809461.90      1562445.47      6809485.77
      1562818.74      6809483.60
#Sta/Elev= 30
  4513.3 1839.73  4614.7 1840.00  4704.8 1839.46  4724.8 1839.88  4733.7 1838.84
  4738.8 1839.12  4744.8 1837.93  4774.9 1836.17  4804.9 1837.28  4824.9 1835.62
  4835.0 1835.22  4875.0 1832.54  4895.0 1831.81  4945.1 1831.41  5001.3 1829.23
  5001.8 1828.73  5008.5 1828.73  5009.0 1829.23  5025.2 1829.93  5045.2 1831.81
  5065.2 1833.12  5085.2 1833.60  5135.2 1833.80  5185.2 1835.03  5235.2 1836.88
  5245.2 1838.41  5255.2 1838.06  5315.2 1838.60  5355.2 1839.33  5368.9 1839.22
#Mann=3,-1,0
  4513.3    0.07       0  5001.3    0.07       0  5009.0    0.07       0
Bank Sta=5001.3,5009
Exp/Cntr=0.3,0.1

Type RM Length L Ch R = 1,2346,197,197,197
BEGIN DESCRIPTION:
Elm 01 12 2346.36
END DESCRIPTION:
XS GIS Cut Line= 3
      1562024.50      6809579.09      1562397.73      6809620.31
      1562729.72      6809598.62
#Sta/Elev= 30
  4619.3 1839.85  4690.2 1839.86  4740.5 1839.37  4770.7 1839.73  4780.8 1839.30
  4790.8 1837.41  4811.0 1835.84  4831.1 1837.06  4841.6 1837.03  4871.3 1834.74
  4921.6 1832.75  4927.4 1831.80  4951.8 1831.09  4971.9 1831.10  4987.0 1829.97
  4987.5 1829.47  4994.3 1829.47  4994.8 1829.97  5012.1 1830.55  5042.2 1832.24
  5082.3 1833.43  5107.1 1833.58  5122.3 1834.13  5142.4 1833.16  5162.4 1833.05
  5182.5 1833.81  5202.5 1834.00  5272.7 1837.45  5282.7 1837.07  5327.5 1839.06
#Mann=3,-1,0
  4619.3    0.07       0  4987.0    0.07       0  4994.8    0.07       0
Bank Sta=4987,4994.8
Exp/Cntr=0.3,0.1

Type RM Length L Ch R = 1,2149,130,130,130
BEGIN DESCRIPTION:
Elm 01 12 2148.74
END DESCRIPTION:
XS GIS Cut Line= 3
      1562104.74      6809837.33      1562415.09      6809789.59
      1562727.58      6809685.42
#Sta/Elev= 30
  4689.6 1839.64  4760.7 1839.36  4770.8 1839.97  4779.9 1837.95  4784.9 1838.11
  4791.0 1837.19  4821.4 1836.05  4861.9 1837.84  4892.2 1834.89  4932.7 1833.80
  4973.2 1829.21  4975.8 1828.18  4976.3 1827.68  4983.1 1827.68  4983.6 1828.18
  4993.4 1829.42  5035.1 1829.83  5045.7 1830.59  5053.5 1832.19  5058.8 1831.60
  5066.8 1832.20  5090.4 1832.70  5185.3 1833.13  5235.4 1834.71  5243.2 1835.54
  5248.5 1835.56  5256.5 1836.61  5274.9 1838.11  5306.5 1838.24  5333.0 1838.88
#Mann=3,-1,0
  4689.6    0.07       0  4975.8    0.07       0  4983.6    0.07       0
Bank Sta=4975.8,4983.6
Exp/Cntr=0.3,0.1

Type RM Length L Ch R = 1,2019,188,188,188
BEGIN DESCRIPTION:
Elm 01 12 2019.24
END DESCRIPTION:
XS GIS Cut Line= 3
      1562161.16      6809956.69      1562493.21      6809887.24
      1562730.99      6809807.26
#Sta/Elev= 30
  4655.2 1839.78  4668.7 1840.06  4679.6 1841.06  4689.8 1840.12  4700.0 1837.26
  4723.8 1835.87  4812.4 1836.76  4868.6 1835.98  4883.9 1835.19  4904.3 1831.52
  4913.4 1828.36  4935.0 1827.53  4959.5 1824.75  4960.0 1824.25  4966.8 1824.25
  4967.3 1824.75  4968.5 1826.02  4986.0 1826.11  5004.7 1825.28  5059.6 1825.79
  5091.3 1829.00  5099.2 1832.13  5104.5 1832.64  5130.7 1833.43  5193.7 1837.90
  5199.0 1837.40  5217.9 1838.25  5225.2 1839.36  5230.5 1838.69  5245.3 1838.59
#Mann=3,-1,0
  4655.2    0.07       0  4959.5    0.07       0  4967.3    0.07       0
Bank Sta=4959.5,4967.3
Exp/Cntr=0.3,0.1

Type RM Length L Ch R = 1,1831,243,243,243
BEGIN DESCRIPTION:
Elm 01 12 1831.21
END DESCRIPTION:
XS GIS Cut Line= 3
      1562237.10      6810180.22      1562547.47      6810063.02
      1562725.38      6809928.50
#Sta/Elev= 30
  4658.7 1838.01  4688.5 1838.22  4742.0 1837.34  4752.7 1837.56  4761.0 1838.80
  4766.4 1838.33  4774.0 1836.49  4791.2 1833.82  4846.3 1832.96  4881.8 1831.57
  4901.3 1831.66  4961.7 1828.44  4967.0 1828.85  5002.7 1828.29  5003.2 1827.79
  5010.0 1827.79  5010.5 1828.29  5029.6 1829.78  5035.7 1829.50  5042.0 1830.26
  5058.1 1830.35  5071.1 1830.46  5077.4 1831.42  5092.0 1831.76  5106.5 1831.41
  5121.1 1831.86  5127.3 1832.63  5135.6 1832.46  5162.9 1834.59  5213.5 1836.32
#Mann=5,-1,0
  4658.7    0.07       0  5002.7    0.07       0  5010.5    0.07       0
  5029.6   0.035       0  5058.1    0.07       0
Bank Sta=5002.7,5010.5
Exp/Cntr=0.3,0.1

Type RM Length L Ch R = 1,1588,216,216,216
BEGIN DESCRIPTION:
Elm 01 12 1588.13
END DESCRIPTION:
XS GIS Cut Line= 3
      1562616.91      6810764.02      1562679.85      6810240.97
      1562734.09      6809915.48
#Sta/Elev= 30
  4469.5 1836.02  4505.8 1836.12  4525.9 1837.14  4566.2 1834.82  4606.5 1834.48
  4662.4 1832.20  4749.5 1831.47  4777.7 1831.83  4797.9 1831.44  4918.8 1831.40
  4969.1 1828.05  4979.2 1826.97  4989.2 1825.01  4995.3 1825.50  4996.9 1824.93
  4997.4 1824.43  5004.2 1824.43  5004.7 1824.93  5009.5 1825.86  5056.6 1827.70
  5061.7 1827.19  5070.3 1828.37  5080.4 1829.05  5118.9 1829.66  5161.5 1830.51
  5222.4 1830.92  5239.1 1832.21  5245.3 1831.75  5273.1 1834.30  5326.3 1836.73
#Mann=5,-1,0
  4469.5    0.07       0  4996.9    0.07       0  5004.7    0.07       0
  5118.9   0.035       0  5245.3    0.07       0
Bank Sta=4996.9,5004.7
Exp/Cntr=0.3,0.1

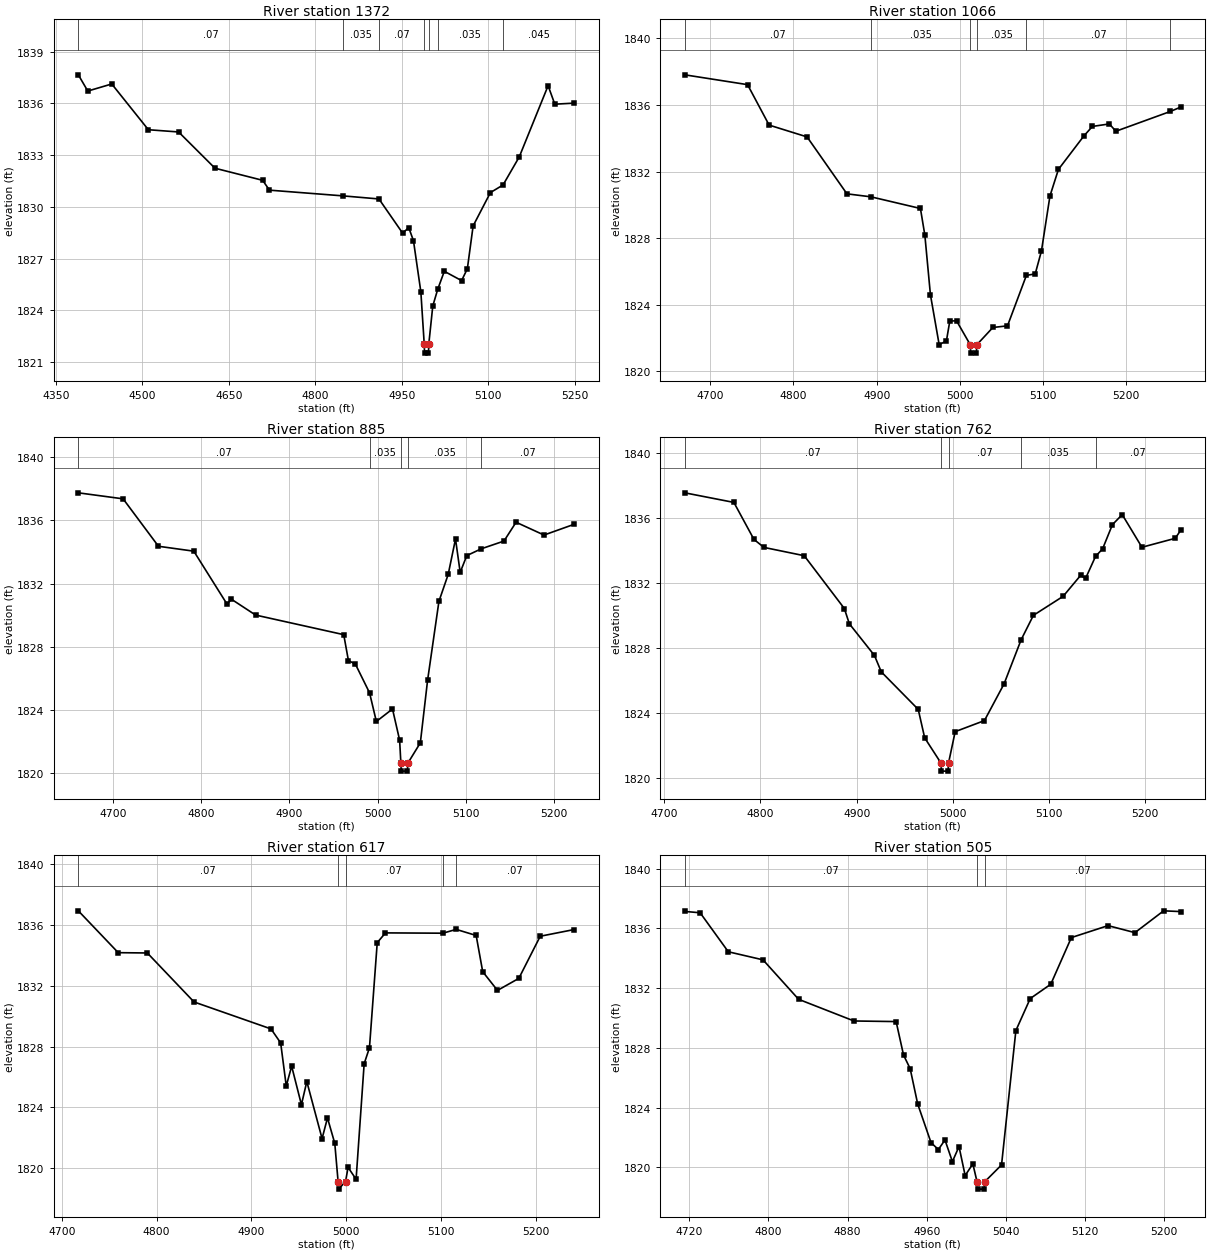
Type RM Length L Ch R = 1,1372,306,306,306
BEGIN DESCRIPTION:
Elm 01 12 1372.19
END DESCRIPTION:
XS GIS Cut Line= 3
      1563029.23      6810683.64      1562842.61      6810104.26
      1562851.28      6809852.81
#Sta/Elev= 30
  4389.0 1837.65  4405.4 1836.71  4447.0 1837.12  4510.5 1834.47  4563.0 1834.34
  4626.1 1832.24  4708.8 1831.54  4720.6 1830.97  4847.6 1830.64  4910.6 1830.46
  4951.7 1828.48  4962.3 1828.80  4970.5 1828.04  4983.3 1825.08  4989.2 1822.03
  4989.7 1821.53  4996.5 1821.53  4997.0 1822.03  5004.0 1824.26  5012.6 1825.23
  5024.0 1826.27  5054.0 1825.73  5064.0 1826.42  5074.0 1828.90  5104.0 1830.83
  5125.9 1831.27  5154.1 1832.90  5204.1 1837.02  5215.7 1835.95  5249.3 1836.01
#Mann=7,-1,0
  4389.0    0.07       0  4847.6   0.035       0  4910.6    0.07       0
  4989.2    0.07       0  4997.0    0.07       0  5012.6   0.035       0
  5125.9   0.045       0
Bank Sta=4989.2,4997
Exp/Cntr=0.3,0.1

Type RM Length L Ch R = 1,1066,181,181,181
BEGIN DESCRIPTION:
Elm 01 12 1066.11
END DESCRIPTION:
XS GIS Cut Line= 3
      1563213.69      6810316.90      1563109.53      6810015.28
      1563055.29      6809744.05
#Sta/Elev= 30
  4669.5 1837.81  4744.9 1837.22  4770.8 1834.79  4816.4 1834.08  4864.3 1830.66
  4893.2 1830.48  4952.6 1829.78  4957.9 1828.18  4964.6 1824.60  4975.1 1821.60
  4983.8 1821.82  4987.9 1823.02  4996.0 1823.03  5012.5 1821.59  5013.0 1821.09
  5019.8 1821.09  5020.3 1821.59  5039.6 1822.63  5057.2 1822.73  5079.9 1825.76
  5090.5 1825.85  5098.0 1827.23  5108.2 1830.53  5118.4 1832.13  5149.0 1834.14
  5159.2 1834.71  5179.6 1834.86  5187.4 1834.42  5252.9 1835.61  5265.2 1835.87
#Mann=6,-1,0
  4669.5    0.07       0  4893.2   0.035       0  5012.5   0.035       0
  5020.3   0.035       0  5079.9    0.07       0  5252.9   0.045       0
Bank Sta=5012.5,5020.3
Exp/Cntr=0.3,0.1

Type RM Length L Ch R = 1,885,123,123,123
BEGIN DESCRIPTION:
Elm 01 12 885.14
END DESCRIPTION:
XS GIS Cut Line= 3
      1563231.71      6810308.65      1563214.35      6810055.21
      1563311.38      6809762.40
#Sta/Elev= 30
  4660.5 1837.75  4711.3 1837.37  4751.4 1834.37  4791.5 1834.06  4829.2 1830.71
  4834.2 1831.02  4861.6 1830.02  4961.6 1828.78  4966.9 1827.14  4974.8 1826.92
  4990.9 1825.10  4998.6 1823.29  5016.9 1824.08  5025.0 1822.11  5026.4 1820.65
  5026.9 1820.15  5033.8 1820.15  5034.3 1820.65  5048.5 1821.94  5056.7 1825.89
  5069.6 1830.89  5080.1 1832.59  5088.4 1834.83  5093.7 1832.72  5101.2 1833.78
  5117.6 1834.21  5143.4 1834.70  5157.1 1835.89  5188.8 1835.08  5223.0 1835.76
#Mann=5,-1,0
  4660.5    0.07       0  4990.9   0.035       0  5026.4   0.035       0
  5034.3   0.035       0  5117.6    0.07       0
Bank Sta=5026.4,5034.3
Exp/Cntr=0.3,0.1

Type RM Length L Ch R = 1,762,145,145,145
BEGIN DESCRIPTION:
Elm 01 12 761.72
END DESCRIPTION:
XS GIS Cut Line= 3
      1563261.24      6810306.91      1563342.82      6810032.64
      1563391.43      6809808.70
#Sta/Elev= 30
  4721.4 1837.54  4772.4 1836.95  4793.3 1834.67  4803.7 1834.18  4845.5 1833.67
  4887.2 1830.42  4892.4 1829.48  4918.5 1827.53  4925.6 1826.52  4964.0 1824.21
  4970.7 1822.46  4987.6 1820.91  4988.1 1820.41  4995.0 1820.41  4995.5 1820.91
  5002.4 1822.84  5032.8 1823.52  5053.2 1825.78  5070.9 1828.49  5083.7 1830.00
  5114.6 1831.17  5132.8 1832.46  5137.9 1832.27  5148.3 1833.63  5155.6 1834.09
  5165.8 1835.58  5176.0 1836.20  5196.5 1834.19  5231.1 1834.74  5236.7 1835.23
#Mann=5,-1,0
  4721.4    0.07       0  4987.6    0.07       0  4995.5    0.07       0
  5070.9   0.035       0  5148.3    0.07       0
Bank Sta=4987.6,4995.5
Exp/Cntr=0.3,0.1

Type RM Length L Ch R = 1,617,112,112,112
BEGIN DESCRIPTION:
Elm 01 12 617.26
END DESCRIPTION:
XS GIS Cut Line= 3
      1563323.72      6810294.81      1563459.14      6810050.00
      1563565.94      6809831.25
#Sta/Elev= 30
  4717.4 1836.92  4759.5 1834.17  4790.2 1834.15  4839.5 1830.93  4920.7 1829.16
  4930.9 1828.24  4936.8 1825.41  4942.5 1826.71  4952.8 1824.18  4958.5 1825.70
  4974.6 1821.95  4980.3 1823.31  4988.0 1821.64  4991.5 1819.13  4992.0 1818.63
  4999.4 1819.13  5002.0 1820.06  5010.5 1819.28  5019.0 1826.87  5024.6 1827.92
  5032.8 1834.83  5041.5 1835.47  5102.1 1835.45  5116.1 1835.70  5137.2 1835.30
  5144.1 1832.92  5159.7 1831.69  5182.2 1832.48  5204.8 1835.25  5240.6 1835.69
#Mann=5,-1,0
  4717.4    0.07       0  4991.5    0.07       0  4999.4    0.07       0
  5102.1   0.035       0  5116.1    0.07       0
Bank Sta=4991.5,4999.4
Exp/Cntr=0.3,0.1

Type RM Length L Ch R = 1,505,159,159,159
BEGIN DESCRIPTION:
Elm 01 12 504.962
END DESCRIPTION:
XS GIS Cut Line= 3
      1563328.97      6810313.86      1563541.59      6810124.67
      1563713.04      6809991.99
#Sta/Elev= 30
  4715.4 1837.13  4730.9 1837.04  4759.4 1834.43  4794.5 1833.89  4830.5 1831.25
  4886.5 1829.80  4929.1 1829.76  4936.6 1827.52  4943.3 1826.61  4950.9 1824.25
  4964.4 1821.66  4971.8 1821.20  4978.5 1821.84  4986.0 1820.39  4992.7 1821.40
  4998.9 1819.46  5006.7 1820.24  5010.9 1819.05  5011.4 1818.55  5018.3 1818.55
  5018.8 1819.05  5035.7 1820.17  5050.2 1829.16  5064.7 1831.30  5085.5 1832.26
  5106.3 1835.38  5143.4 1836.18  5170.6 1835.71  5199.6 1837.17  5216.8 1837.12
#Mann=3,-1,0
  4715.4    0.07       0  5010.9    0.07       0  5018.8    0.07       0
Bank Sta=5010.9,5018.8
Exp/Cntr=0.3,0.1

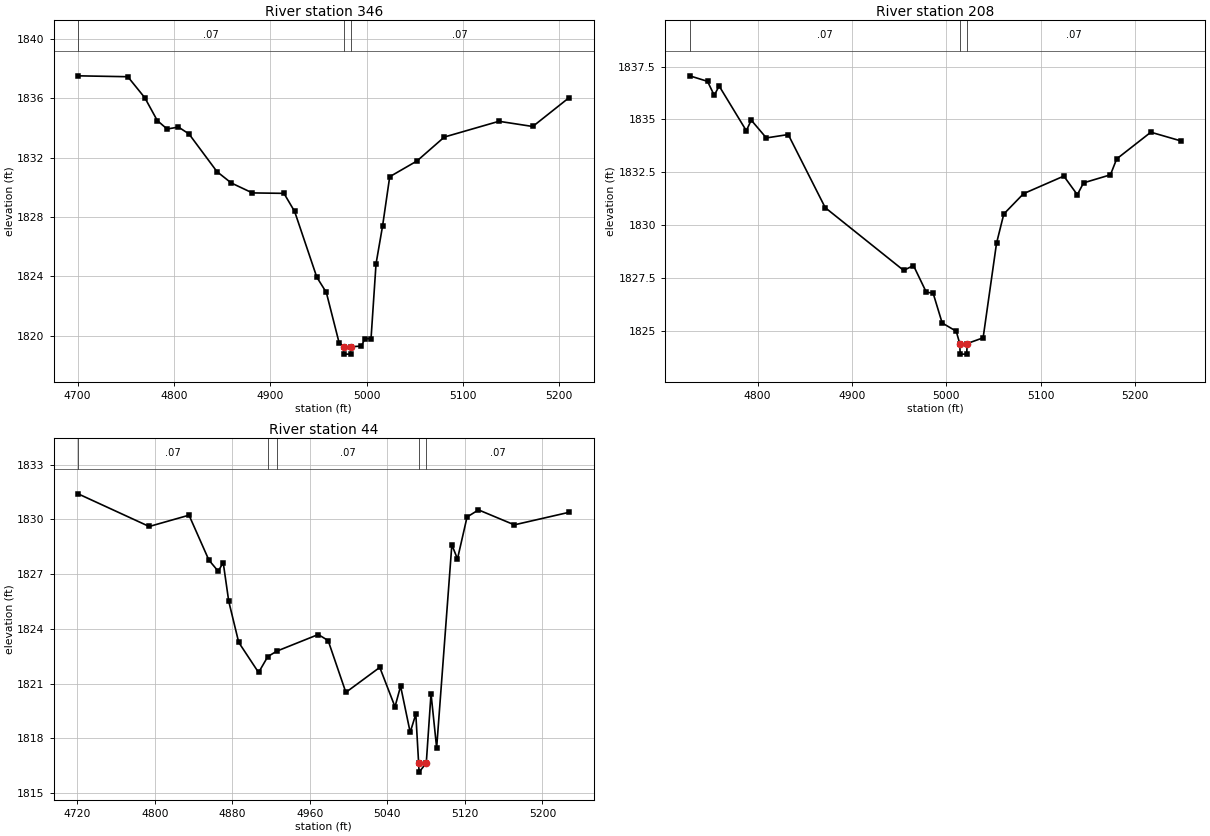
Type RM Length L Ch R = 1,346,138,138,138
BEGIN DESCRIPTION:
Elm 01 12 3597
END DESCRIPTION:
XS GIS Cut Line= 3
      1563330.03      6810372.91      1563603.02      6810249.97
      1563757.77      6810107.27
#Sta/Elev= 30
  4700.6 1837.50  4752.2 1837.44  4769.9 1836.02  4782.8 1834.49  4793.0 1833.92
  4804.8 1834.05  4815.7 1833.59  4844.8 1831.05  4859.6 1830.29  4881.5 1829.62
  4914.3 1829.59  4925.4 1828.37  4948.4 1823.95  4958.3 1822.92  4971.5 1819.55
  4976.3 1819.27  4976.8 1818.77  4983.7 1818.77  4984.2 1819.27  4994.7 1819.31
  4998.3 1819.81  5004.7 1819.81  5009.9 1824.85  5016.7 1827.40  5024.1 1830.71
  5052.4 1831.77  5080.8 1833.38  5137.5 1834.44  5172.6 1834.09  5210.5 1836.04
#Mann=3,-1,0
  4700.6    0.07       0  4976.3    0.07       0  4984.2    0.07       0
Bank Sta=4976.3,4984.2
Exp/Cntr=0.3,0.1

Type RM Length L Ch R = 1,208,164,164,164
BEGIN DESCRIPTION:
Elm 01 12 3593
END DESCRIPTION:
XS GIS Cut Line= 3
      1563346.81      6810460.58      1563608.49      6810386.73
      1563796.75      6810224.53
#Sta/Elev= 30
  4728.1 1837.06  4747.0 1836.80  4754.1 1836.14  4759.3 1836.58  4788.1 1834.47
  4793.3 1834.97  4809.3 1834.13  4832.5 1834.29  4871.7 1830.84  4954.8 1827.88
  4965.2 1828.11  4978.8 1826.85  4986.0 1826.81  4995.6 1825.40  5010.5 1825.01
  5014.2 1824.43  5014.7 1823.93  5021.6 1823.93  5022.1 1824.43  5039.0 1824.70
  5053.2 1829.16  5060.9 1830.54  5081.8 1831.50  5124.5 1832.33  5138.8 1831.45
  5145.4 1832.01  5173.9 1832.39  5180.5 1833.14  5216.7 1834.40  5248.5 1833.99
#Mann=3,-1,0
  4728.1    0.07       0  5014.2    0.07       0  5022.1    0.07       0
Bank Sta=5014.2,5022.1
Exp/Cntr=0.3,0.1

Type RM Length L Ch R = 1,44,0,0,0
BEGIN DESCRIPTION:
Elm 01 12 3591
END DESCRIPTION:
XS GIS Cut Line= 3
      1563433.46      6810556.49      1563705.63      6810493.78
      1563820.36      6810297.10
#Sta/Elev= 30
  4720.7 1831.40  4794.1 1829.61  4835.2 1830.23  4855.7 1827.77  4865.3 1827.16
  4870.5 1827.63  4876.2 1825.51  4886.5 1823.26  4907.0 1821.61  4916.5 1822.48
  4925.8 1822.78  4968.6 1823.69  4978.8 1823.36  4997.1 1820.52  5032.1 1821.89
  5047.8 1819.73  5053.6 1820.86  5063.5 1818.33  5069.3 1819.33  5072.2 1816.65
  5072.7 1816.15  5080.1 1816.65  5085.0 1820.45  5090.8 1817.48  5106.5 1828.61
  5112.3 1827.83  5122.2 1830.13  5134.0 1830.52  5171.0 1829.70  5227.7 1830.39
#Mann=5,-1,0
  4720.7    0.07       0  4916.5    0.16       0  4925.8    0.07       0
  5072.2    0.07       0  5080.1    0.07       0
Bank Sta=5072.2,5080.1
Exp/Cntr=0.3,0.1

Chan Stop Cuts=-1