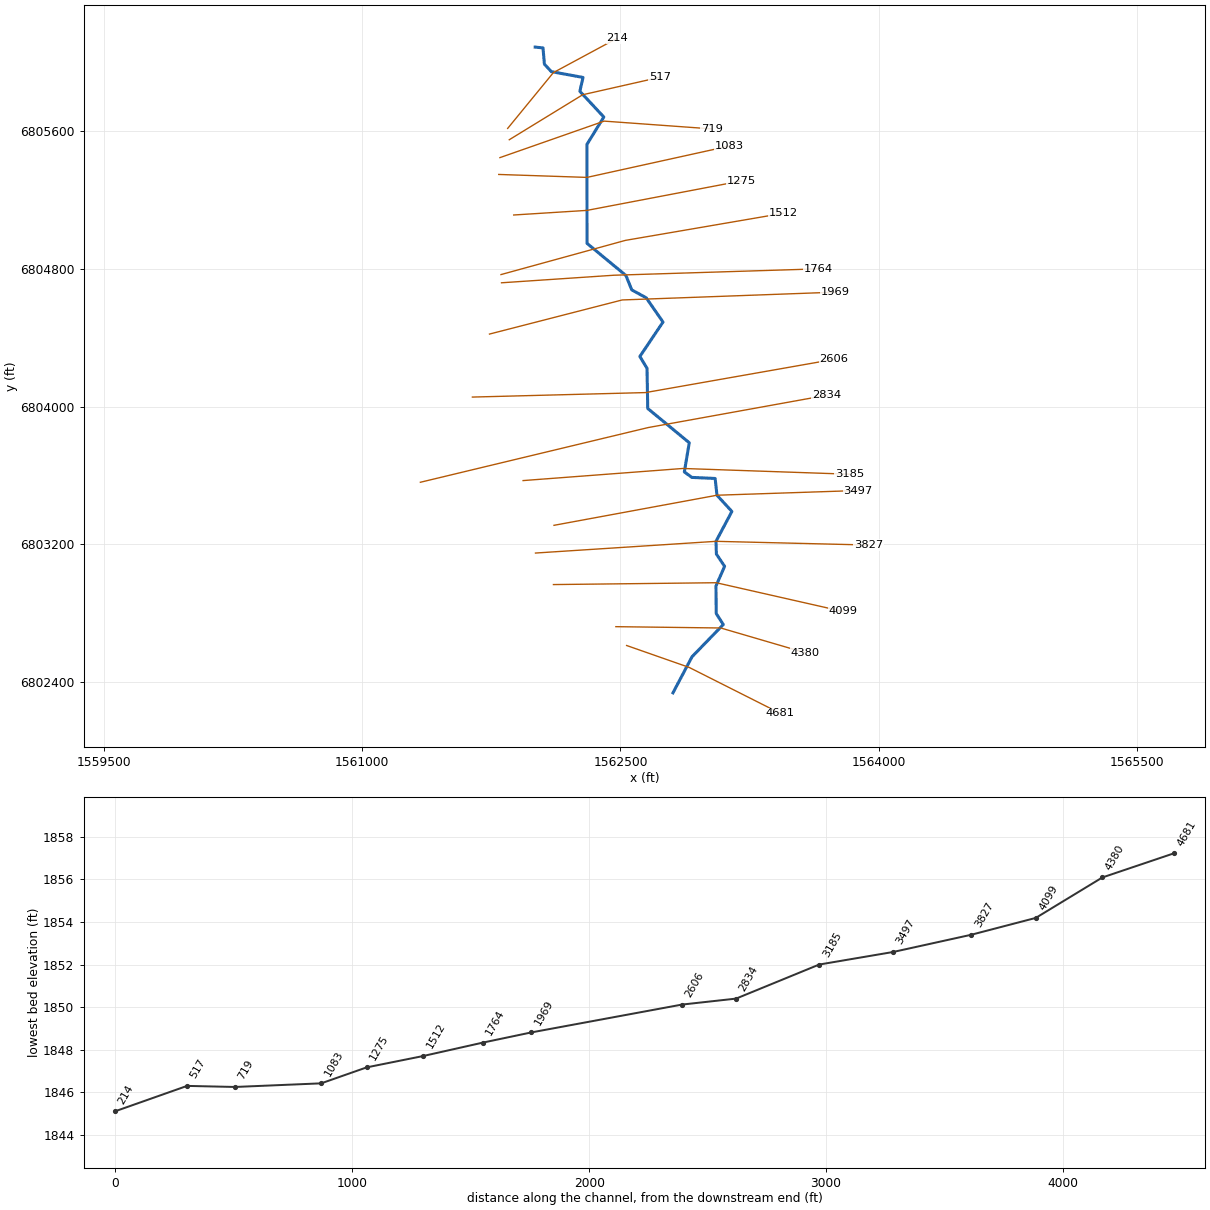
--- Elm 01 13.prj (project) ---

Proj Title=Elm 01 13 Base Level Engineering
Current Plan=p01
Default Exp/Contr=0.3,0.1
English Units
Geom File=g01
Flow File=f01
Plan File=p01
BEGIN DESCRIPTION:
Elm 01 13
END DESCRIPTION:

--- Elm 01 13.p01 (plan) ---

Plan Title=Multiple Run
Short Identifier=Multiple
Geom File=g01
Flow File=f01
Subcritical Flow
K Sum by GR= 0
Std Step Tol= 0.01
Critical Tol= 0.01
Num of Std Step Trials= 20
Max Error Tol= 0.3
Flow Tol Ratio= 0.001
Split Flow NTrial= 30
Split Flow Tol= 0.02
Split Flow Ratio= 0.02
Log Output Level= 0
Friction Slope Method= 1
Unsteady Friction Slope Method= 2
Unsteady Bridges Friction Slope Method= 1
Parabolic Critical Depth
Global Vel Dist=  1 , 1 , 1
Global Log Level= 0
CheckData=True
Encroach Param= -1, 0, 0, 0
BEGIN DESCRIPTION:
Multiple Run
END DESCRIPTION:

--- Elm 01 13.f01 (steady flow) ---

Flow Title=Multiple
Number of Profiles=7
Profile Names=10-year,25-year,50-year,1pct_min,100-year,1pct_plu,500-year
River Rch & RM= Elm 01 13,Reach-1,4681
     168     225     270     201     323     444     465
Boundary for River Rch & Prof#=Elm 01 13,Reach-1,1
Up Type=0
Dn Type=3
Dn Slope=0.005
Boundary for River Rch & Prof#=Elm 01 13,Reach-1,2
Up Type=0
Dn Type=3
Dn Slope=0.005
Boundary for River Rch & Prof#=Elm 01 13,Reach-1,3
Up Type=0
Dn Type=3
Dn Slope=0.005
Boundary for River Rch & Prof#=Elm 01 13,Reach-1,4
Up Type=0
Dn Type=3
Dn Slope=0.005
Boundary for River Rch & Prof#=Elm 01 13,Reach-1,5
Up Type=0
Dn Type=3
Dn Slope=0.005
Boundary for River Rch & Prof#=Elm 01 13,Reach-1,6
Up Type=0
Dn Type=3
Dn Slope=0.005
Boundary for River Rch & Prof#=Elm 01 13,Reach-1,7
Up Type=0
Dn Type=3
Dn Slope=0.005

--- Elm 01 13.g01 (geometry) ---

Geom Title=Existing Conditions

River Reach=Elm 01 13,Reach-1
Reach XY= 30
      1562805.00      6802338.00      1562915.76      6802547.68
      1563097.21      6802734.58      1563056.39      6802798.43
      1563054.65      6802958.15      1563104.91      6803072.61
      1563057.19      6803143.97      1563054.89      6803217.91
      1563147.22      6803391.40      1563060.58      6803485.64
      1563049.92      6803582.96      1562915.12      6803589.06
      1562871.10      6803620.83      1562899.61      6803790.44
      1562658.53      6803989.45      1562654.34      6804222.84
      1562612.81      6804291.41      1562747.22      6804491.40
      1562649.35      6804632.37      1562565.70      6804678.03
      1562531.98      6804761.46      1562305.99      6804948.28
      1562305.39      6805522.84      1562403.42      6805681.95
      1562264.31      6805831.34      1562282.69      6805911.83
      1562098.48      6805945.68      1562058.47      6805989.27
      1562050.25      6806083.32      1562005.00      6806088.00

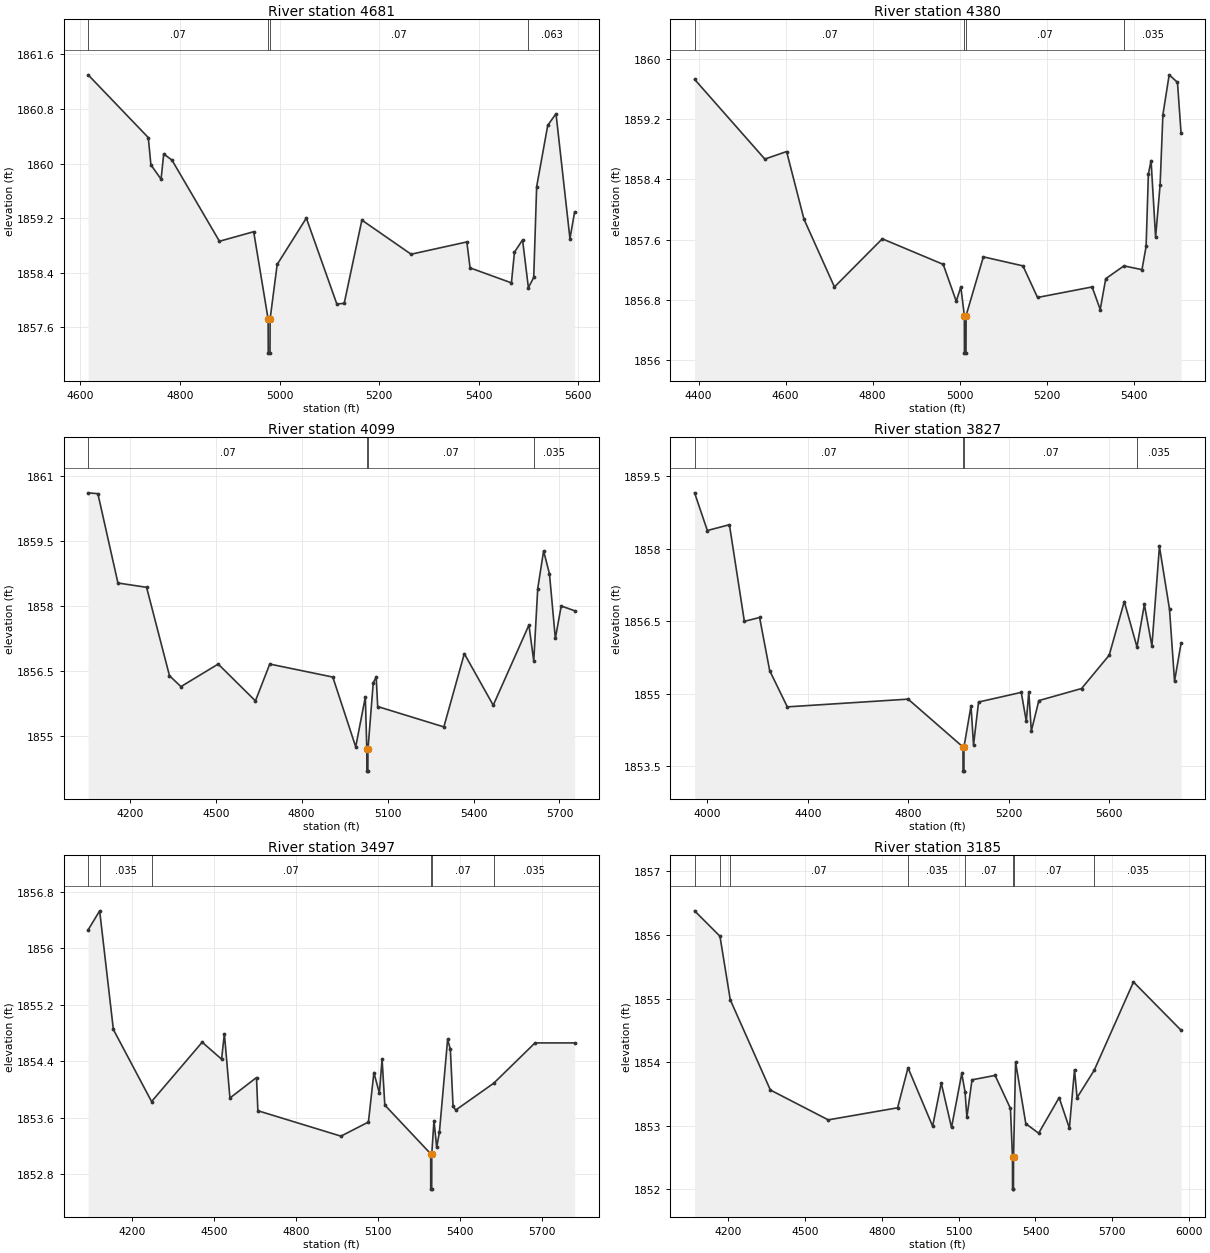
Type RM Length L Ch R = 1,4681,301,301,301
BEGIN DESCRIPTION:
Elm 01 13 3669
END DESCRIPTION:
XS GIS Cut Line= 3
      1562535.93      6802612.95      1562898.90      6802485.81
      1563428.37      6802218.77
#Sta/Elev= 30
  4615.4 1861.30  4736.3 1860.38  4741.6 1859.98  4762.0 1859.77  4767.3 1860.14
  4783.9 1860.05  4879.3 1858.86  4948.1 1859.00  4977.1 1857.72  4977.4 1857.22
  4980.9 1857.22  4981.1 1857.72  4995.3 1858.52  5053.9 1859.20  5115.2 1857.94
  5130.0 1857.95  5165.5 1859.17  5264.4 1858.67  5376.4 1858.85  5382.9 1858.47
  5466.0 1858.25  5472.1 1858.70  5488.4 1858.88  5500.1 1858.18  5510.8 1858.33
  5516.7 1859.66  5539.0 1860.56  5555.6 1860.73  5583.6 1858.90  5593.0 1859.29
#Mann=4,-1,0
  4615.4    0.07       0  4977.1    0.07       0  4981.1    0.07       0
  5500.1   0.063       0
Bank Sta=4977.1,4981.1
Exp/Cntr=0.3,0.1

Type RM Length L Ch R = 1,4380,281,281,281
BEGIN DESCRIPTION:
Elm 01 13 3667
END DESCRIPTION:
XS GIS Cut Line= 3
      1562473.50      6802722.31      1563082.55      6802714.64
      1563571.25      6802571.61
#Sta/Elev= 30
  4390.9 1859.73  4552.4 1858.67  4602.4 1858.77  4642.4 1857.87  4712.4 1856.97
  4822.4 1857.61  4962.4 1857.27  4992.4 1856.78  5002.9 1856.97  5011.0 1856.59
  5011.2 1856.09  5014.7 1856.09  5015.0 1856.59  5054.7 1857.37  5145.7 1857.25
  5179.2 1856.83  5304.7 1856.97  5323.3 1856.67  5336.0 1857.08  5377.8 1857.25
  5419.3 1857.20  5428.8 1857.51  5434.0 1858.47  5440.2 1858.65  5450.6 1857.63
  5461.0 1858.33  5467.4 1859.26  5481.8 1859.79  5500.9 1859.69  5509.2 1859.01
#Mann=4,-1,0
  4390.9    0.07       0  5011.0    0.07       0  5015.0    0.07       0
  5377.8   0.035       0
Bank Sta=5011,5015
Exp/Cntr=0.3,0.1

Type RM Length L Ch R = 1,4099,272,272,272
BEGIN DESCRIPTION:
Elm 01 13 3665
END DESCRIPTION:
XS GIS Cut Line= 3
      1562110.90      6802966.78      1563056.24      6802977.50
      1563790.59      6802810.98
#Sta/Elev= 30
  4054.6 1860.61  4088.7 1860.59  4158.7 1858.53  4258.7 1858.43  4338.7 1856.39
  4378.7 1856.14  4508.7 1856.66  4638.7 1855.81  4688.7 1856.66  4908.8 1856.36
  4988.8 1854.75  5022.4 1855.90  5027.5 1854.69  5027.7 1854.19  5031.2 1854.19
  5031.5 1854.69  5050.0 1856.23  5060.3 1856.36  5065.5 1855.68  5296.5 1855.21
  5367.9 1856.90  5468.9 1855.71  5593.5 1857.56  5610.3 1856.73  5624.2 1858.40
  5644.7 1859.27  5665.2 1858.74  5685.7 1857.25  5706.2 1858.00  5753.0 1857.89
#Mann=4,-1,0
  4054.6    0.07       0  5027.5    0.07       0  5031.5    0.07       0
  5610.3   0.035       0
Bank Sta=5027.5,5031.5
Exp/Cntr=0.3,0.1

Type RM Length L Ch R = 1,3827,330,330,330
BEGIN DESCRIPTION:
Elm 01 13 3663
END DESCRIPTION:
XS GIS Cut Line= 3
      1562006.60      6803149.88      1563054.89      6803217.91
      1563941.13      6803196.30
#Sta/Elev= 30
  3949.5 1859.16  4000.3 1858.38  4088.2 1858.50  4147.7 1856.50  4208.4 1856.58
  4248.5 1855.48  4318.7 1854.73  4799.7 1854.89  5018.1 1853.90  5018.4 1853.40
  5021.9 1853.40  5022.1 1853.90  5050.1 1854.75  5060.1 1853.94  5080.1 1854.83
  5250.2 1855.03  5270.2 1854.43  5280.2 1855.04  5290.2 1854.23  5320.2 1854.86
  5490.3 1855.11  5600.3 1855.80  5660.3 1856.91  5710.8 1855.97  5740.3 1856.85
  5770.3 1855.99  5800.3 1858.05  5840.4 1856.75  5860.4 1855.26  5886.5 1856.05
#Mann=4,-1,0
  3949.5    0.07       0  5018.1    0.07       0  5022.1    0.07       0
  5710.8   0.035       0
Bank Sta=5018.1,5022.1
Exp/Cntr=0.3,0.1

Type RM Length L Ch R = 1,3497,312,312,312
BEGIN DESCRIPTION:
Elm 01 13 3661
END DESCRIPTION:
XS GIS Cut Line= 3
      1562114.08      6803310.85      1563060.58      6803485.64
      1563880.02      6803513.00
#Sta/Elev= 30
  4037.5 1856.26  4079.8 1856.53  4130.0 1854.85  4270.0 1853.83  4455.4 1854.67
  4526.5 1854.43  4536.7 1854.79  4557.1 1853.88  4654.4 1854.17  4659.4 1853.70
  4963.8 1853.34  5064.5 1853.54  5084.5 1854.24  5104.5 1853.95  5114.5 1854.43
  5124.5 1853.78  5292.6 1853.09  5292.8 1852.59  5296.3 1852.59  5296.6 1853.09
  5304.6 1853.56  5314.6 1853.18  5324.6 1853.40  5354.6 1854.71  5364.6 1854.57
  5374.6 1853.76  5384.6 1853.71  5523.7 1854.09  5674.8 1854.66  5819.9 1854.66
#Mann=6,-1,0
  4037.5    0.07       0  4079.8   0.035       0  4270.0    0.07       0
  5292.6    0.07       0  5296.6    0.07       0  5523.7   0.035       0
Bank Sta=5292.6,5296.6
Exp/Cntr=0.3,0.1

Type RM Length L Ch R = 1,3185,351,351,351
BEGIN DESCRIPTION:
Elm 01 13 3377.748
END DESCRIPTION:
XS GIS Cut Line= 3
      1561934.65      6803570.66      1562862.79      6803641.01
      1563830.81      6803607.58
#Sta/Elev= 30
  4069.2 1856.38  4168.3 1855.98  4208.5 1854.98  4365.1 1853.56  4591.0 1853.09
  4861.8 1853.28  4902.5 1853.91  4998.6 1852.99  5032.2 1853.67  5072.3 1852.97
  5112.3 1853.82  5125.2 1853.53  5132.3 1853.13  5152.3 1853.72  5242.4 1853.79
  5302.4 1853.27  5310.4 1852.50  5310.6 1852.00  5314.1 1852.00  5314.4 1852.50
  5322.4 1854.00  5362.4 1853.03  5412.5 1852.88  5492.5 1853.44  5532.5 1852.96
  5552.5 1853.88  5562.5 1853.44  5629.3 1853.87  5782.7 1855.26  5968.6 1854.50
#Mann=8,-1,0
  4069.2    0.07       0  4168.3   0.035       0  4208.5    0.07       0
  4902.5   0.035       0  5125.2    0.07       0  5310.4   0.035       0
  5314.4    0.07       0  5629.3   0.035       0
Bank Sta=5310.4,5314.4
Exp/Cntr=0.3,0.1

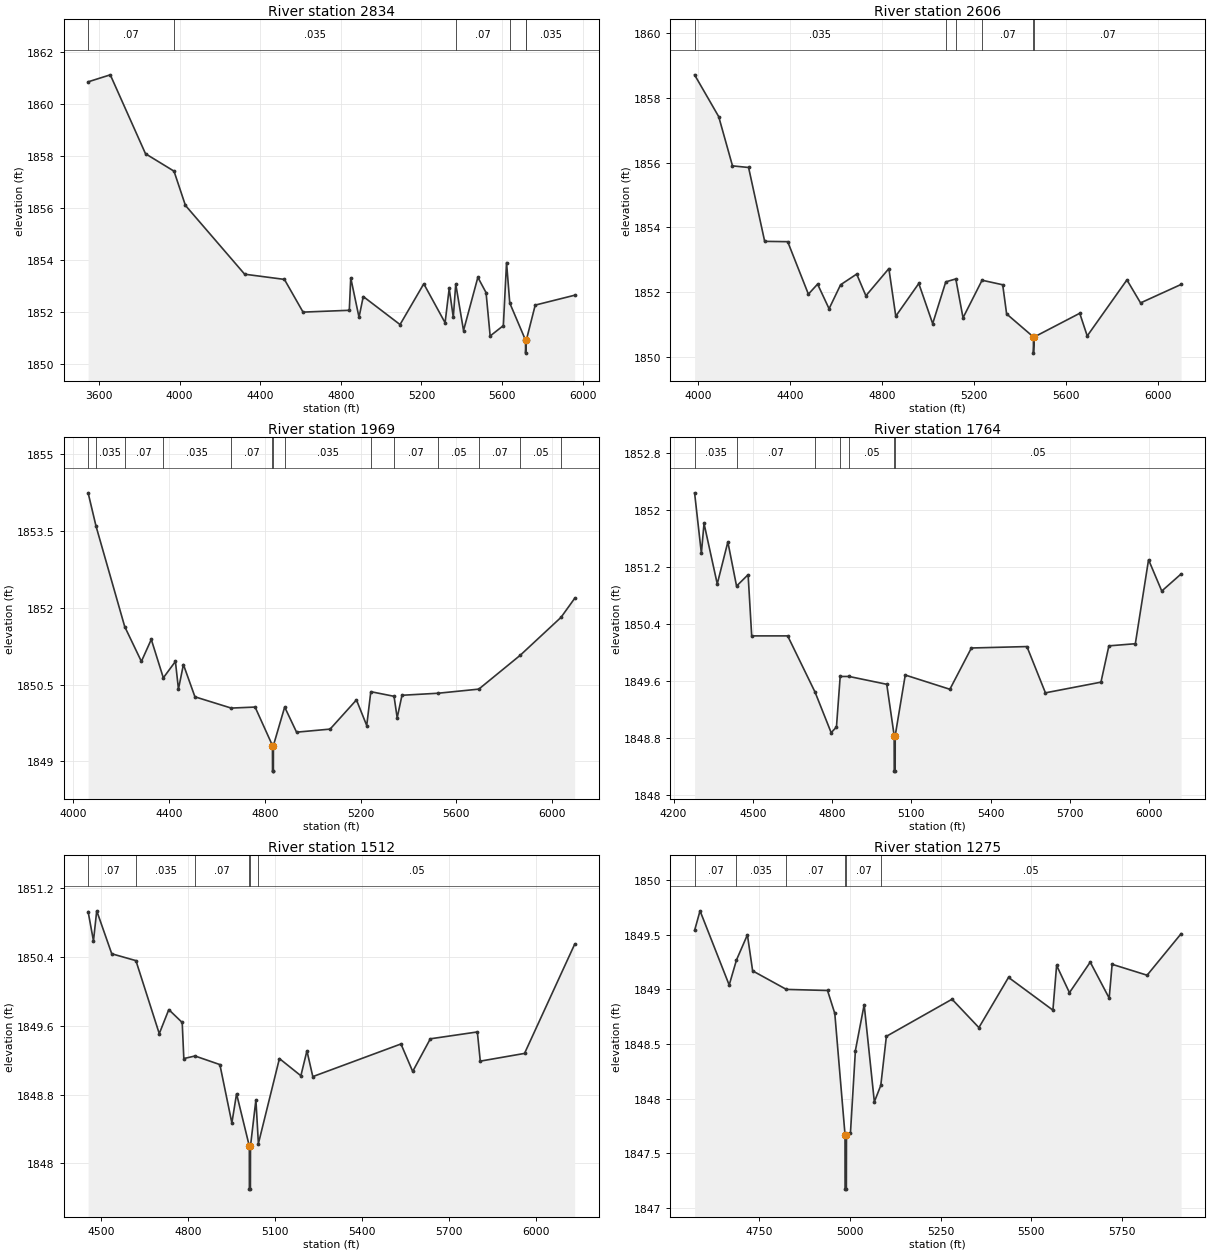
Type RM Length L Ch R = 1,2834,228,228,228
BEGIN DESCRIPTION:
Elm 01 13 2834.38
END DESCRIPTION:
XS GIS Cut Line= 3
      1561338.04      6803560.85      1562660.97      6803878.56
      1563697.40      6804066.06
#Sta/Elev= 30
  3546.0 1860.85  3656.0 1861.12  3830.8 1858.08  3972.1 1857.41  4028.8 1856.09
  4322.7 1853.44  4519.9 1853.24  4612.4 1851.98  4841.9 1852.05  4849.0 1853.30
  4890.1 1851.78  4911.1 1852.58  5093.6 1851.50  5211.4 1853.07  5317.1 1851.57
  5337.5 1852.89  5357.8 1851.78  5370.0 1853.06  5408.6 1851.27  5479.7 1853.32
  5520.4 1852.73  5540.7 1851.06  5606.2 1851.46  5622.0 1853.89  5638.0 1852.33
  5716.2 1850.90  5716.5 1850.40  5720.2 1850.90  5764.3 1852.25  5959.8 1852.63
#Mann=6,-1,0
  3546.0    0.07       0  3972.1   0.035       0  5370.0    0.07       0
  5638.0   0.035       0  5716.2   0.035       0  5720.2   0.035       0
Bank Sta=5716.2,5720.2
Exp/Cntr=0.3,0.1

Type RM Length L Ch R = 1,2606,637,637,637
BEGIN DESCRIPTION:
Elm 01 13 2606.12
END DESCRIPTION:
XS GIS Cut Line= 3
      1561640.17      6804055.65      1562645.34      6804081.69
      1563739.09      6804274.39
#Sta/Elev= 30
  3985.2 1858.71  4090.1 1857.42  4150.1 1855.90  4220.1 1855.85  4290.1 1853.57
  4390.2 1853.56  4480.2 1851.94  4520.2 1852.25  4570.2 1851.49  4620.2 1852.23
  4690.3 1852.56  4730.3 1851.89  4830.3 1852.73  4860.3 1851.26  4960.4 1852.27
  5020.8 1851.03  5077.8 1852.32  5121.4 1852.41  5152.8 1851.21  5235.6 1852.37
  5325.4 1852.23  5342.4 1851.33  5458.9 1850.62  5459.2 1850.12  5462.9 1850.62
  5660.5 1851.35  5693.0 1850.65  5865.7 1852.38  5925.0 1851.67  6101.3 1852.24
#Mann=6,-1,0
  3985.2   0.035       0  5077.8    0.07       0  5121.4   0.035       0
  5235.6    0.07       0  5458.9   0.035       0  5462.9    0.07       0
Bank Sta=5458.9,5462.9
Exp/Cntr=0.3,0.1

Type RM Length L Ch R = 1,1969,205,205,205
BEGIN DESCRIPTION:
Elm 01 13 1971.726
END DESCRIPTION:
XS GIS Cut Line= 3
      1561739.55      6804421.52      1562510.12      6804619.63
      1563745.56      6804664.80
#Sta/Elev= 30
  4061.8 1854.24  4094.8 1853.59  4214.6 1851.63  4284.3 1850.95  4325.6 1851.38
  4375.9 1850.63  4426.4 1850.95  4439.1 1850.41  4459.8 1850.89  4507.9 1850.26
  4659.5 1850.04  4759.2 1850.06  4831.7 1849.31  4832.0 1848.81  4835.5 1848.81
  4835.7 1849.31  4882.7 1850.06  4932.4 1849.57  5072.5 1849.63  5182.5 1850.20
  5225.4 1849.70  5242.5 1850.36  5339.5 1850.27  5352.6 1849.85  5372.7 1850.29
  5524.0 1850.33  5693.5 1850.41  5866.4 1851.07  6036.8 1851.81  6093.7 1852.18
#Mann=14,-1,0
  4061.8    0.07       0  4094.8   0.035       0  4214.6    0.07       0
  4375.9   0.035       0  4659.5    0.07       0  4831.7   0.035       0
  4835.7    0.07       0  4882.7   0.035       0  5242.5    0.05       0
  5339.5    0.07       0  5524.0    0.05       0  5693.5    0.07       0
  5866.4    0.05       0  6036.8    0.07       0
Bank Sta=4831.7,4835.7
Exp/Cntr=0.3,0.1

Type RM Length L Ch R = 1,1764,252,252,252
BEGIN DESCRIPTION:
Elm 01 13 3655
END DESCRIPTION:
XS GIS Cut Line= 3
      1561809.40      6804719.31      1562460.46      6804763.10
      1563648.05      6804800.20
#Sta/Elev= 30
  4279.7 1852.24  4305.4 1851.39  4315.4 1851.81  4365.5 1850.96  4405.6 1851.55
  4438.5 1850.93  4482.2 1851.09  4495.8 1850.23  4631.9 1850.23  4735.5 1849.44
  4796.5 1848.87  4816.5 1848.95  4830.6 1849.66  4864.1 1849.66  5006.8 1849.55
  5034.8 1848.83  5035.1 1848.33  5038.6 1848.33  5038.8 1848.83  5076.8 1849.68
  5245.6 1849.48  5327.0 1850.06  5537.1 1850.08  5607.1 1849.43  5817.2 1849.58
  5847.2 1850.09  5947.3 1850.12  5997.3 1851.30  6047.3 1850.86  6120.4 1851.10
#Mann=7,-1,0
  4279.7   0.035       0  4438.5    0.07       0  4735.5   0.035       0
  4830.6    0.07       0  4864.1    0.05       0  5034.8    0.05       0
  5038.8    0.05       0
Bank Sta=5034.8,5038.8
Exp/Cntr=0.3,0.1

Type RM Length L Ch R = 1,1512,237,237,237
BEGIN DESCRIPTION:
Elm 01 13 3653
END DESCRIPTION:
XS GIS Cut Line= 3
      1561806.32      6804766.97      1562529.15      6804965.68
      1563446.10      6805123.01
#Sta/Elev= 30
  4454.8 1850.93  4473.3 1850.59  4484.5 1850.94  4536.4 1850.44  4619.9 1850.36
  4700.5 1849.51  4733.4 1849.79  4779.7 1849.64  4785.3 1849.22  4823.9 1849.25
  4909.8 1849.15  4951.2 1848.47  4967.4 1848.81  5011.5 1848.20  5011.7 1847.70
  5015.2 1847.70  5015.5 1848.20  5034.2 1848.74  5042.8 1848.23  5115.4 1849.22
  5189.5 1849.02  5210.4 1849.31  5230.7 1849.01  5535.1 1849.39  5575.6 1849.07
  5636.5 1849.45  5798.9 1849.53  5809.0 1849.19  5961.8 1849.28  6134.8 1850.55
#Mann=6,-1,0
  4454.8    0.07       0  4619.9   0.035       0  4823.9    0.07       0
  5011.5    0.07       0  5015.5    0.07       0  5042.8    0.05       0
Bank Sta=5011.5,5015.5
Exp/Cntr=0.3,0.1

Type RM Length L Ch R = 1,1275,192,192,192
BEGIN DESCRIPTION:
Elm 01 13 3651
END DESCRIPTION:
XS GIS Cut Line= 3
      1561880.03      6805113.00      1562305.79      6805139.80
      1563201.34      6805310.61
#Sta/Elev= 30
  4573.4 1849.54  4588.4 1849.72  4668.6 1849.04  4688.7 1849.27  4718.7 1849.50
  4733.1 1849.17  4825.9 1849.00  4939.1 1848.99  4959.1 1848.78  4987.2 1847.67
  4987.4 1847.17  4990.9 1847.17  4991.2 1847.67  5002.1 1847.68  5015.8 1848.44
  5039.9 1848.86  5067.9 1847.97  5085.6 1848.12  5101.0 1848.57  5281.6 1848.91
  5355.5 1848.65  5437.0 1849.11  5559.1 1848.81  5569.3 1849.22  5604.6 1848.97
  5661.8 1849.25  5713.9 1848.92  5722.0 1849.23  5818.2 1849.13  5911.7 1849.51
#Mann=6,-1,0
  4573.4    0.07       0  4688.7   0.035       0  4825.9    0.07       0
  4987.2    0.07       0  4991.2    0.07       0  5085.6    0.05       0
Bank Sta=4987.2,4991.2
Exp/Cntr=0.3,0.1

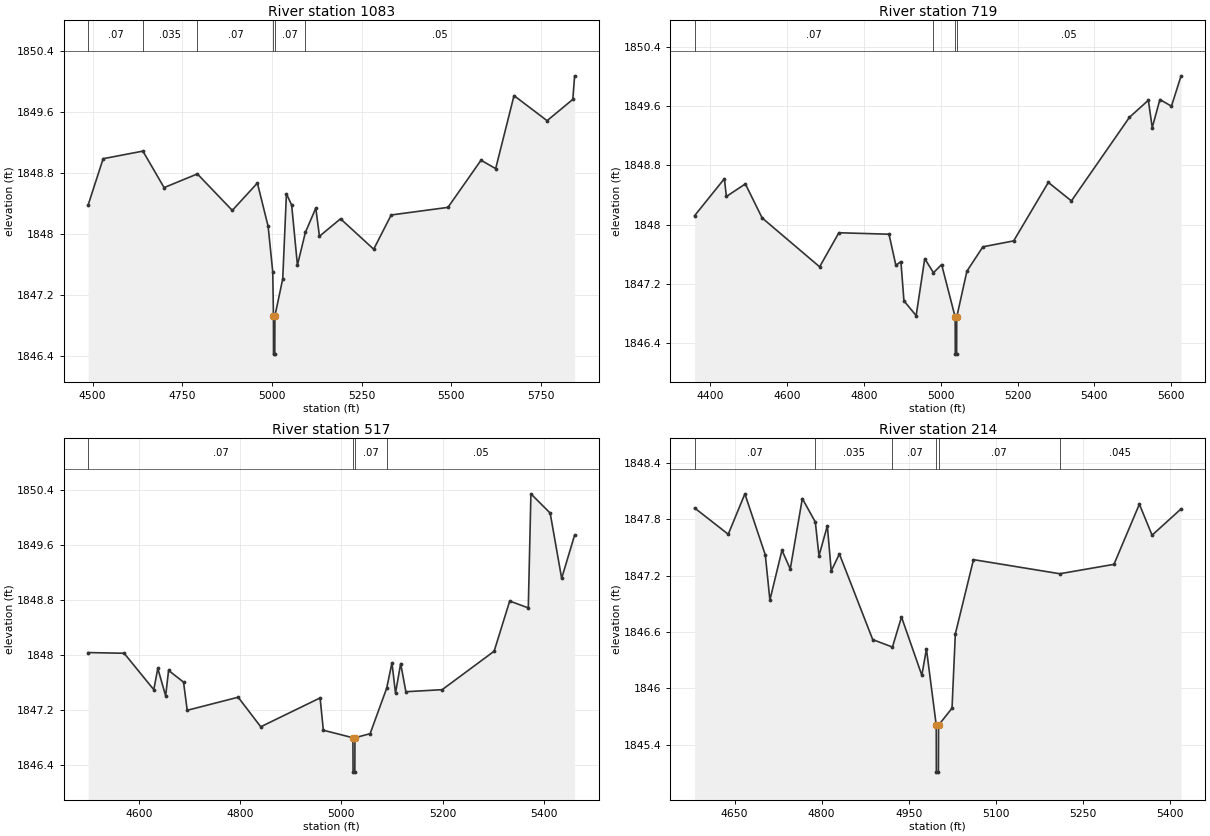
Type RM Length L Ch R = 1,1083,364,364,364
BEGIN DESCRIPTION:
Elm 01 13 3646
END DESCRIPTION:
XS GIS Cut Line= 3
      1561793.17      6805348.46      1562305.59      6805331.32
      1563130.01      6805513.00
#Sta/Elev= 30
  4487.3 1848.38  4529.2 1848.99  4640.1 1849.09  4699.2 1848.61  4792.0 1848.79
  4889.4 1848.31  4959.4 1848.67  4989.4 1848.10  5002.3 1847.50  5004.2 1846.92
  5004.4 1846.42  5007.9 1846.42  5008.2 1846.92  5030.1 1847.41  5040.4 1848.53
  5055.0 1848.38  5071.1 1847.59  5093.2 1848.02  5122.3 1848.34  5132.5 1847.97
  5191.3 1848.20  5283.8 1847.80  5332.6 1848.25  5490.9 1848.35  5583.1 1848.97
  5624.0 1848.86  5675.2 1849.82  5767.4 1849.49  5839.1 1849.77  5844.2 1850.08
#Mann=6,-1,0
  4487.3    0.07       0  4640.1   0.035       0  4792.0    0.07       0
  5004.2    0.07       0  5008.2    0.07       0  5093.2    0.05       0
Bank Sta=5004.2,5008.2
Exp/Cntr=0.3,0.1

Type RM Length L Ch R = 1,719,202,202,202
BEGIN DESCRIPTION:
Elm 01 13 3643
END DESCRIPTION:
XS GIS Cut Line= 3
      1561800.12      6805446.17      1562405.47      6805658.16
      1563030.04      6805613.00
#Sta/Elev= 30
  4358.6 1848.12  4436.2 1848.62  4441.5 1848.38  4490.9 1848.55  4534.6 1848.09
  4684.4 1847.43  4734.6 1847.89  4865.2 1847.87  4883.0 1847.45  4896.2 1847.50
  4904.1 1846.97  4935.9 1846.77  4958.3 1847.54  4981.0 1847.35  5002.3 1847.46
  5037.6 1846.75  5037.9 1846.25  5041.4 1846.25  5041.6 1846.75  5068.1 1847.37
  5109.8 1847.70  5190.0 1847.78  5280.3 1848.57  5340.4 1848.32  5491.7 1849.45
  5540.9 1849.68  5551.0 1849.31  5571.0 1849.69  5601.1 1849.60  5626.2 1850.01
#Mann=4,-1,0
  4358.6    0.07       0  4981.0    0.05       0  5037.6    0.05       0
  5041.6    0.05       0
Bank Sta=5037.6,5041.6
Exp/Cntr=0.3,0.1

Type RM Length L Ch R = 1,517,303,303,303
BEGIN DESCRIPTION:
Elm 01 13 3642
END DESCRIPTION:
XS GIS Cut Line= 3
      1561854.38      6805550.02      1562280.78      6805811.34
      1562730.02      6805913.00
#Sta/Elev= 30
  4499.9 1848.04  4571.0 1848.03  4629.6 1847.50  4637.5 1847.81  4653.0 1847.41
  4658.8 1847.78  4688.3 1847.61  4695.6 1847.20  4796.2 1847.39  4840.8 1846.96
  4958.0 1847.38  4964.4 1846.91  5022.8 1846.80  5023.1 1846.30  5026.6 1846.30
  5026.8 1846.80  5056.8 1846.86  5089.4 1847.52  5099.9 1847.89  5106.9 1847.45
  5117.1 1847.88  5127.4 1847.47  5199.1 1847.50  5301.7 1848.06  5332.4 1848.79
  5369.1 1848.69  5374.3 1850.35  5412.3 1850.07  5435.0 1849.12  5460.6 1849.75
#Mann=4,-1,0
  4499.9    0.07       0  5022.8    0.07       0  5026.8    0.07       0
  5089.4    0.05       0
Bank Sta=5022.8,5026.8
Exp/Cntr=0.3,0.1

Type RM Length L Ch R = 1,214,0,0,0
BEGIN DESCRIPTION:
Elm 01 13 3631
END DESCRIPTION:
XS GIS Cut Line= 3
      1561845.14      6805615.85      1562110.65      6805939.98
      1562479.98      6806138.92
#Sta/Elev= 30
  4581.0 1847.92  4639.0 1847.64  4667.7 1848.07  4702.9 1847.42  4710.8 1846.94
  4731.6 1847.47  4745.9 1847.27  4766.7 1848.02  4789.1 1847.77  4795.4 1847.41
  4809.8 1847.73  4816.5 1847.25  4830.6 1847.43  4888.0 1846.52  4922.0 1846.44
  4937.6 1846.76  4972.7 1846.14  4980.6 1846.42  4997.5 1845.61  4997.7 1845.11
  5001.2 1845.11  5001.5 1845.61  5024.7 1845.79  5030.4 1846.58  5061.7 1847.37
  5210.4 1847.22  5303.8 1847.32  5347.6 1847.96  5369.5 1847.63  5419.5 1847.91
#Mann=6,-1,0
  4581.0    0.07       0  4789.1   0.035       0  4922.0    0.07       0
  4997.5    0.07       0  5001.5    0.07       0  5210.4   0.045       0
Bank Sta=4997.5,5001.5
Exp/Cntr=0.3,0.1

Chan Stop Cuts=-1