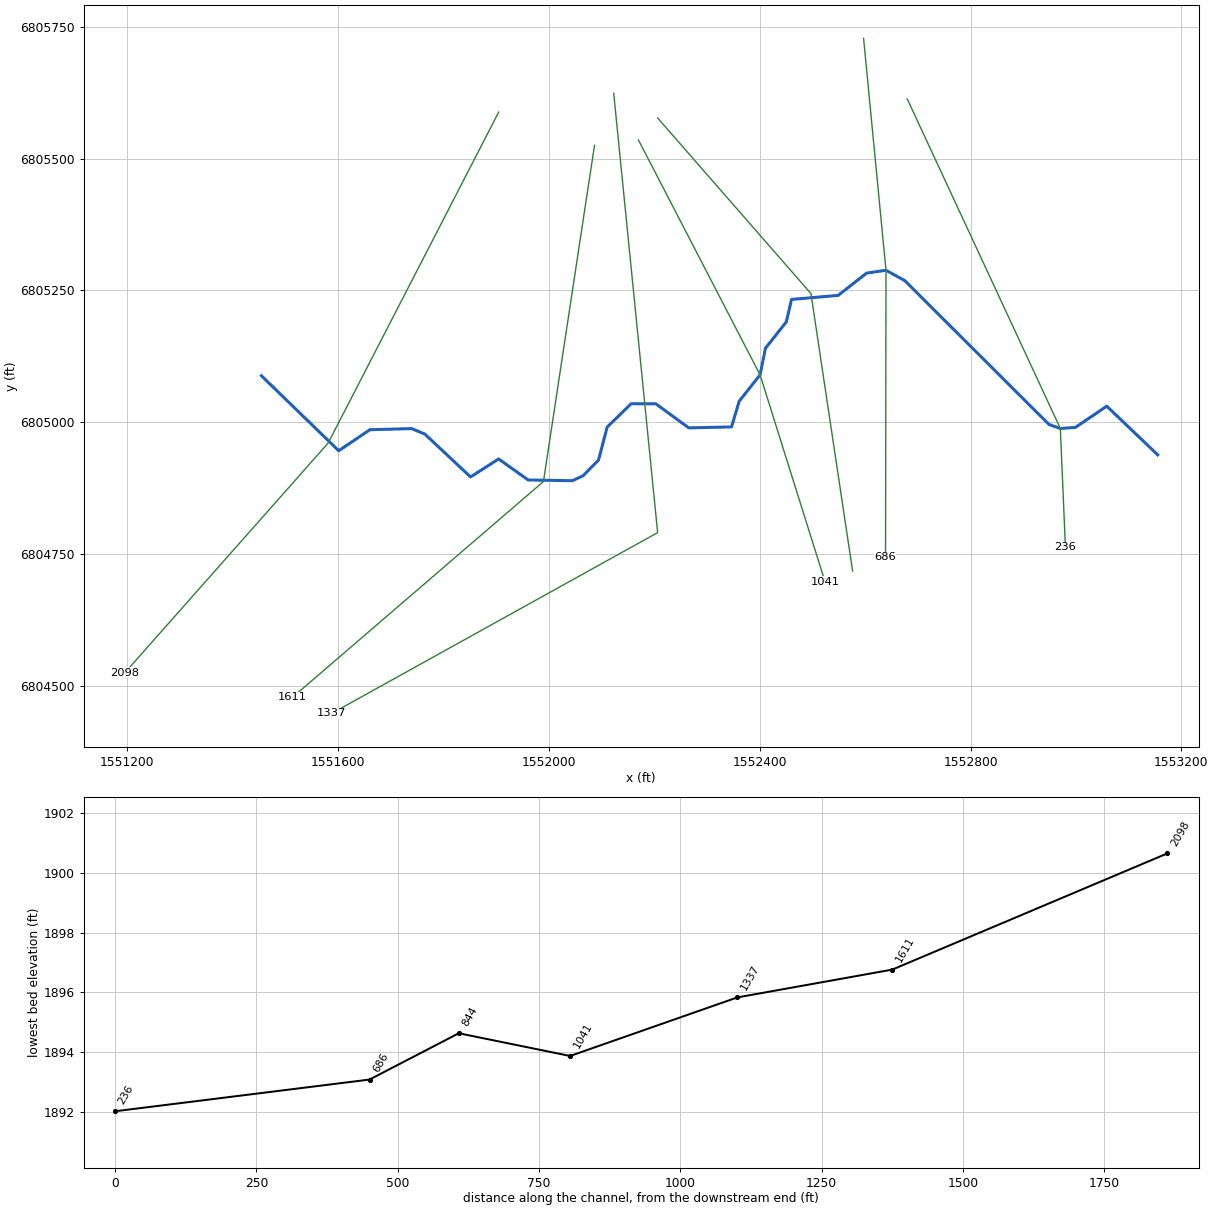
--- Elm 01 15.prj (project) ---

Proj Title=Elm 01 15 Base Level Engineering
Current Plan=p01
Default Exp/Contr=0.3,0.1
English Units
Geom File=g01
Flow File=f01
Plan File=p01
BEGIN DESCRIPTION:
Elm 01 15
END DESCRIPTION:

--- Elm 01 15.p01 (plan) ---

Plan Title=Multiple Run
Short Identifier=Multiple
Geom File=g01
Flow File=f01
Subcritical Flow
K Sum by GR= 0
Std Step Tol= 0.01
Critical Tol= 0.01
Num of Std Step Trials= 20
Max Error Tol= 0.3
Flow Tol Ratio= 0.001
Split Flow NTrial= 30
Split Flow Tol= 0.02
Split Flow Ratio= 0.02
Log Output Level= 0
Friction Slope Method= 1
Unsteady Friction Slope Method= 2
Unsteady Bridges Friction Slope Method= 1
Parabolic Critical Depth
Global Vel Dist=  1 , 1 , 1
Global Log Level= 0
CheckData=True
Encroach Param= -1, 0, 0, 0
BEGIN DESCRIPTION:
Multiple Run
END DESCRIPTION:

--- Elm 01 15.f01 (steady flow) ---

Flow Title=Multiple
Number of Profiles=7
Profile Names=10-year,25-year,50-year,1pct_min,100-year,1pct_plu,500-year
River Rch & RM= Elm 01 15,Reach-1,2098
     190     257     312     234     375     517     552
Boundary for River Rch & Prof#=Elm 01 15,Reach-1,1
Up Type=0
Dn Type=3
Dn Slope=0.005
Boundary for River Rch & Prof#=Elm 01 15,Reach-1,2
Up Type=0
Dn Type=3
Dn Slope=0.005
Boundary for River Rch & Prof#=Elm 01 15,Reach-1,3
Up Type=0
Dn Type=3
Dn Slope=0.005
Boundary for River Rch & Prof#=Elm 01 15,Reach-1,4
Up Type=0
Dn Type=3
Dn Slope=0.005
Boundary for River Rch & Prof#=Elm 01 15,Reach-1,5
Up Type=0
Dn Type=3
Dn Slope=0.005
Boundary for River Rch & Prof#=Elm 01 15,Reach-1,6
Up Type=0
Dn Type=3
Dn Slope=0.005
Boundary for River Rch & Prof#=Elm 01 15,Reach-1,7
Up Type=0
Dn Type=3
Dn Slope=0.005

--- Elm 01 15.g01 (geometry) ---

Geom Title=Existing Conditions

River Reach=Elm 01 15,Reach-1
Reach XY= 30
      1551455.00      6805088.00      1551601.58      6804945.79
      1551660.89      6804985.63      1551739.78      6804987.74
      1551764.79      6804977.52      1551851.67      6804896.01
      1551904.90      6804930.19      1551960.90      6804890.35
      1552044.67      6804888.88      1552065.10      6804898.31
      1552094.37      6804927.96      1552110.76      6804990.59
      1552156.42      6805034.96      1552203.23      6805034.67
      1552265.65      6804989.08      1552346.68      6804990.97
      1552361.27      6805039.78      1552400.85      6805089.69
      1552411.06      6805140.23      1552450.63      6805190.17
      1552460.44      6805232.75      1552548.95      6805240.42
      1552602.83      6805282.65      1552639.66      6805288.05
      1552675.09      6805268.57      1552948.95      6804995.50
      1552970.36      6804988.01      1552998.95      6804989.98
      1553058.41      6805030.30      1553155.00      6804938.00

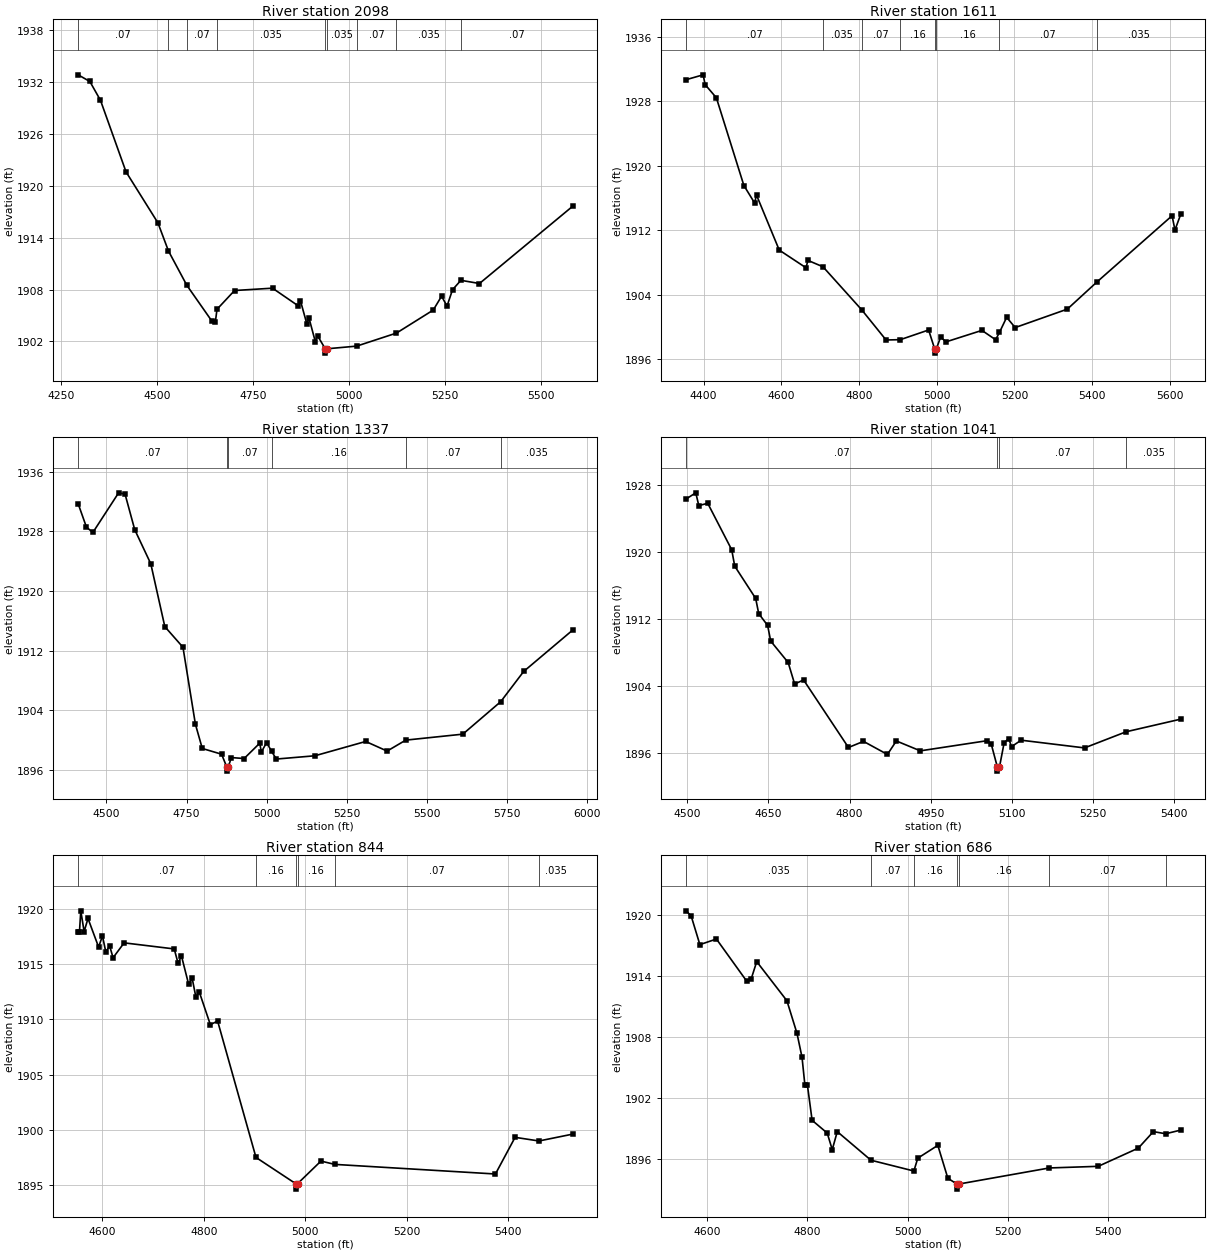
Type RM Length L Ch R = 1,2098,487,487,487
BEGIN DESCRIPTION:
Elm 01 15 2018.344
END DESCRIPTION:
XS GIS Cut Line= 3
      1551905.01      6805588.02      1551581.64      6804960.43
      1551196.12      6804524.83
#Sta/Elev= 30
  4294.0 1932.83  4324.5 1932.06  4352.2 1929.88  4418.7 1921.61  4501.8 1915.71
  4529.2 1912.46  4577.1 1908.49  4642.8 1904.32  4651.3 1904.24  4655.6 1905.72
  4701.3 1907.89  4800.2 1908.16  4867.4 1906.11  4873.0 1906.69  4889.5 1904.04
  4895.1 1904.72  4911.7 1901.96  4917.3 1902.67  4937.5 1901.15  4937.7 1900.65
  4941.5 1901.15  5019.3 1901.46  5123.0 1902.97  5218.7 1905.63  5240.4 1907.23
  5254.6 1906.09  5268.9 1907.98  5290.7 1909.07  5339.1 1908.70  5581.7 1917.63
#Mann=9,-1,0
  4294.0    0.07       0  4529.2   0.035       0  4577.1    0.07       0
  4655.6   0.035       0  4937.5   0.035       0  4941.5   0.035       0
  5019.3    0.07       0  5123.0   0.035       0  5290.7    0.07       0
Bank Sta=4937.5,4941.5
Exp/Cntr=0.3,0.1

Type RM Length L Ch R = 1,1611,274,274,274
BEGIN DESCRIPTION:
Elm 01 15 1534.181
END DESCRIPTION:
XS GIS Cut Line= 3
      1552086.74      6805524.82      1551989.93      6804887.33
      1551513.83      6804477.95
#Sta/Elev= 30
  4355.2 1930.68  4398.8 1931.28  4403.9 1930.07  4432.9 1928.43  4503.7 1917.55
  4531.2 1915.39  4536.2 1916.36  4594.7 1909.54  4663.5 1907.35  4668.6 1908.26
  4707.3 1907.47  4806.8 1902.14  4869.6 1898.39  4906.3 1898.43  4979.1 1899.63
  4994.9 1897.26  4995.2 1896.76  4998.9 1897.26  5009.9 1898.74  5024.1 1898.16
  5116.3 1899.58  5151.6 1898.42  5161.4 1899.33  5180.0 1901.20  5201.9 1899.93
  5336.2 1902.22  5412.7 1905.60  5605.7 1913.80  5613.2 1912.03  5627.9 1913.97
#Mann=8,-1,0
  4355.2    0.07       0  4707.3   0.035       0  4806.8    0.07       0
  4906.3    0.16       0  4994.9    0.07       0  4998.9    0.16       0
  5161.4    0.07       0  5412.7   0.035       0
Bank Sta=4994.9,4998.9
Exp/Cntr=0.3,0.1

Type RM Length L Ch R = 1,1337,296,296,296
BEGIN DESCRIPTION:
Elm 01 15 3599
END DESCRIPTION:
XS GIS Cut Line= 3
      1552123.20      6805623.80      1552206.54      6804790.45
      1551588.35      6804447.59
#Sta/Elev= 30
  4411.5 1931.71  4437.4 1928.57  4457.5 1927.85  4537.9 1933.17  4558.0 1933.00
  4588.2 1928.23  4638.4 1923.65  4682.2 1915.22  4738.9 1912.45  4777.7 1902.13
  4799.2 1898.87  4859.5 1898.10  4876.2 1896.33  4876.4 1895.83  4880.2 1896.33
  4889.7 1897.65  4929.9 1897.52  4978.7 1899.58  4983.7 1898.40  5000.2 1899.66
  5015.7 1898.49  5030.4 1897.45  5151.0 1897.89  5309.6 1899.81  5376.5 1898.52
  5434.7 1899.99  5612.9 1900.79  5731.3 1905.15  5802.9 1909.20  5955.9 1914.75
#Mann=6,-1,0
  4411.5    0.07       0  4876.2    0.07       0  4880.2    0.07       0
  5015.7    0.16       0  5434.7    0.07       0  5731.3   0.035       0
Bank Sta=4876.2,4880.2
Exp/Cntr=0.3,0.1

Type RM Length L Ch R = 1,1041,197,197,197
BEGIN DESCRIPTION:
Elm 01 15 3596
END DESCRIPTION:
XS GIS Cut Line= 3
      1552170.07      6805535.27      1552400.85      6805089.69
      1552524.24      6804696.71
#Sta/Elev= 30
  4498.2 1926.34  4515.9 1927.07  4521.5 1925.55  4538.0 1925.82  4582.3 1920.28
  4587.9 1918.32  4626.6 1914.47  4632.2 1912.66  4648.7 1911.25  4654.3 1909.39
  4686.6 1906.83  4698.6 1904.26  4715.1 1904.75  4798.0 1896.69  4825.8 1897.42
  4870.0 1895.86  4886.5 1897.47  4930.8 1896.29  5054.2 1897.50  5061.7 1897.13
  5073.1 1894.37  5073.4 1893.87  5077.1 1894.37  5085.6 1897.23  5094.1 1897.76
  5099.3 1896.79  5117.1 1897.56  5234.2 1896.64  5311.3 1898.57  5411.9 1900.07
#Mann=4,-1,0
  4498.2    0.07       0  5073.1    0.07       0  5077.1    0.07       0
  5311.3   0.035       0
Bank Sta=5073.1,5077.1
Exp/Cntr=0.3,0.1

Type RM Length L Ch R = 1,844,158,158,158
BEGIN DESCRIPTION:
Elm 01 15 3594
END DESCRIPTION:
XS GIS Cut Line= 3
      1552206.57      6805576.88      1552497.32      6805243.86
      1552576.33      6804717.55
#Sta/Elev= 30
  4552.6 1917.91  4555.2 1917.91  4557.8 1919.83  4564.4 1917.95  4572.0 1919.14
  4592.9 1916.55  4600.5 1917.56  4607.1 1916.11  4614.7 1916.65  4621.4 1915.58
  4643.2 1916.93  4741.9 1916.38  4749.5 1915.08  4756.2 1915.74  4770.4 1913.16
  4777.1 1913.76  4784.7 1911.99  4791.3 1912.48  4813.1 1909.52  4827.4 1909.85
  4903.0 1897.50  4981.1 1895.13  4981.3 1894.63  4985.1 1895.13  5031.0 1897.17
  5058.2 1896.87  5374.8 1896.00  5413.5 1899.32  5460.6 1898.99  5526.9 1899.61
#Mann=6,-1,0
  4552.6    0.07       0  4903.0    0.16       0  4981.1    0.07       0
  4985.1    0.16       0  5058.2    0.07       0  5460.6   0.035       0
Bank Sta=4981.1,4985.1
Exp/Cntr=0.3,0.1

Type RM Length L Ch R = 1,686,450,450,450
BEGIN DESCRIPTION:
Elm 01 15 3592
END DESCRIPTION:
XS GIS Cut Line= 3
      1552597.16      6805728.00      1552639.66      6805288.05
      1552638.83      6804743.55
#Sta/Elev= 30
  4558.0 1920.42  4568.0 1919.90  4585.3 1917.10  4618.3 1917.65  4678.6 1913.52
  4687.6 1913.72  4698.7 1915.43  4758.9 1911.59  4779.0 1908.39  4789.1 1906.03
  4794.8 1903.30  4799.8 1903.31  4809.2 1899.84  4839.3 1898.59  4849.4 1896.96
  4859.4 1898.73  4926.6 1895.92  5012.2 1894.86  5020.0 1896.12  5060.0 1897.38
  5080.0 1894.15  5098.0 1893.58  5098.3 1893.08  5102.0 1893.58  5282.4 1895.16
  5380.0 1895.32  5460.0 1897.11  5490.0 1898.73  5514.5 1898.52  5544.5 1898.88
#Mann=7,-1,0
  4558.0   0.035       0  4926.6    0.07       0  5012.2    0.16       0
  5098.0    0.07       0  5102.0    0.16       0  5282.4    0.07       0
  5514.5   0.035       0
Bank Sta=5098,5102
Exp/Cntr=0.3,0.1

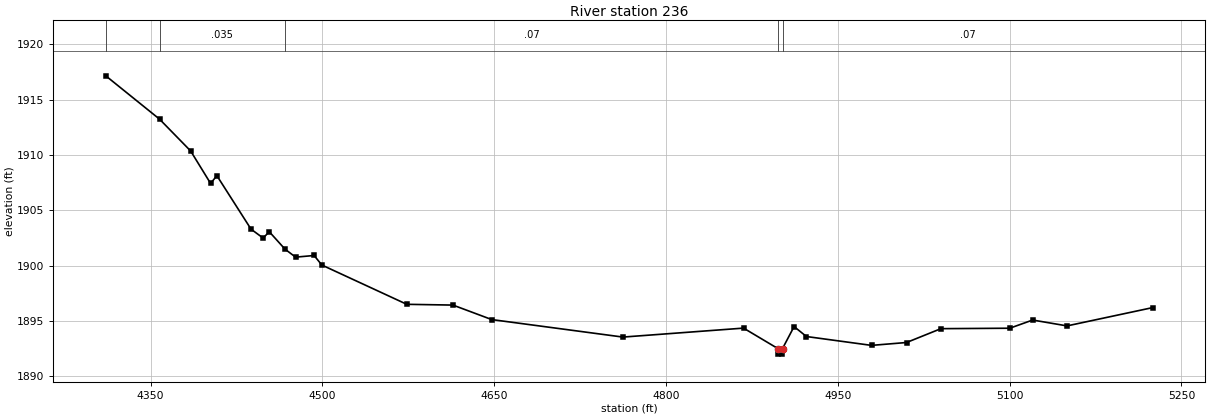
Type RM Length L Ch R = 1,236,0,0,0
BEGIN DESCRIPTION:
Elm 01 15 3587
END DESCRIPTION:
XS GIS Cut Line= 3
      1552680.02      6805612.96      1552970.36      6804988.01
      1552980.00      6804763.02
#Sta/Elev= 30
  4310.9 1917.16  4357.8 1913.25  4385.0 1910.37  4402.4 1907.44  4407.9 1908.14
  4437.7 1903.31  4448.2 1902.51  4453.7 1903.07  4467.3 1901.51  4476.6 1900.78
  4492.8 1900.93  4499.5 1900.07  4573.7 1896.52  4614.0 1896.45  4647.9 1895.14
  4762.4 1893.56  4867.7 1894.37  4897.7 1892.52  4898.0 1892.02  4901.5 1892.02
  4901.7 1892.52  4911.8 1894.51  4922.6 1893.61  4979.4 1892.81  5010.0 1893.07
  5040.0 1894.32  5100.1 1894.36  5120.1 1895.10  5150.1 1894.57  5225.2 1896.23
#Mann=5,-1,0
  4310.9    0.07       0  4357.8   0.035       0  4467.3    0.07       0
  4897.7    0.07       0  4901.7    0.07       0
Bank Sta=4897.7,4901.7
Exp/Cntr=0.3,0.1

Chan Stop Cuts=-1