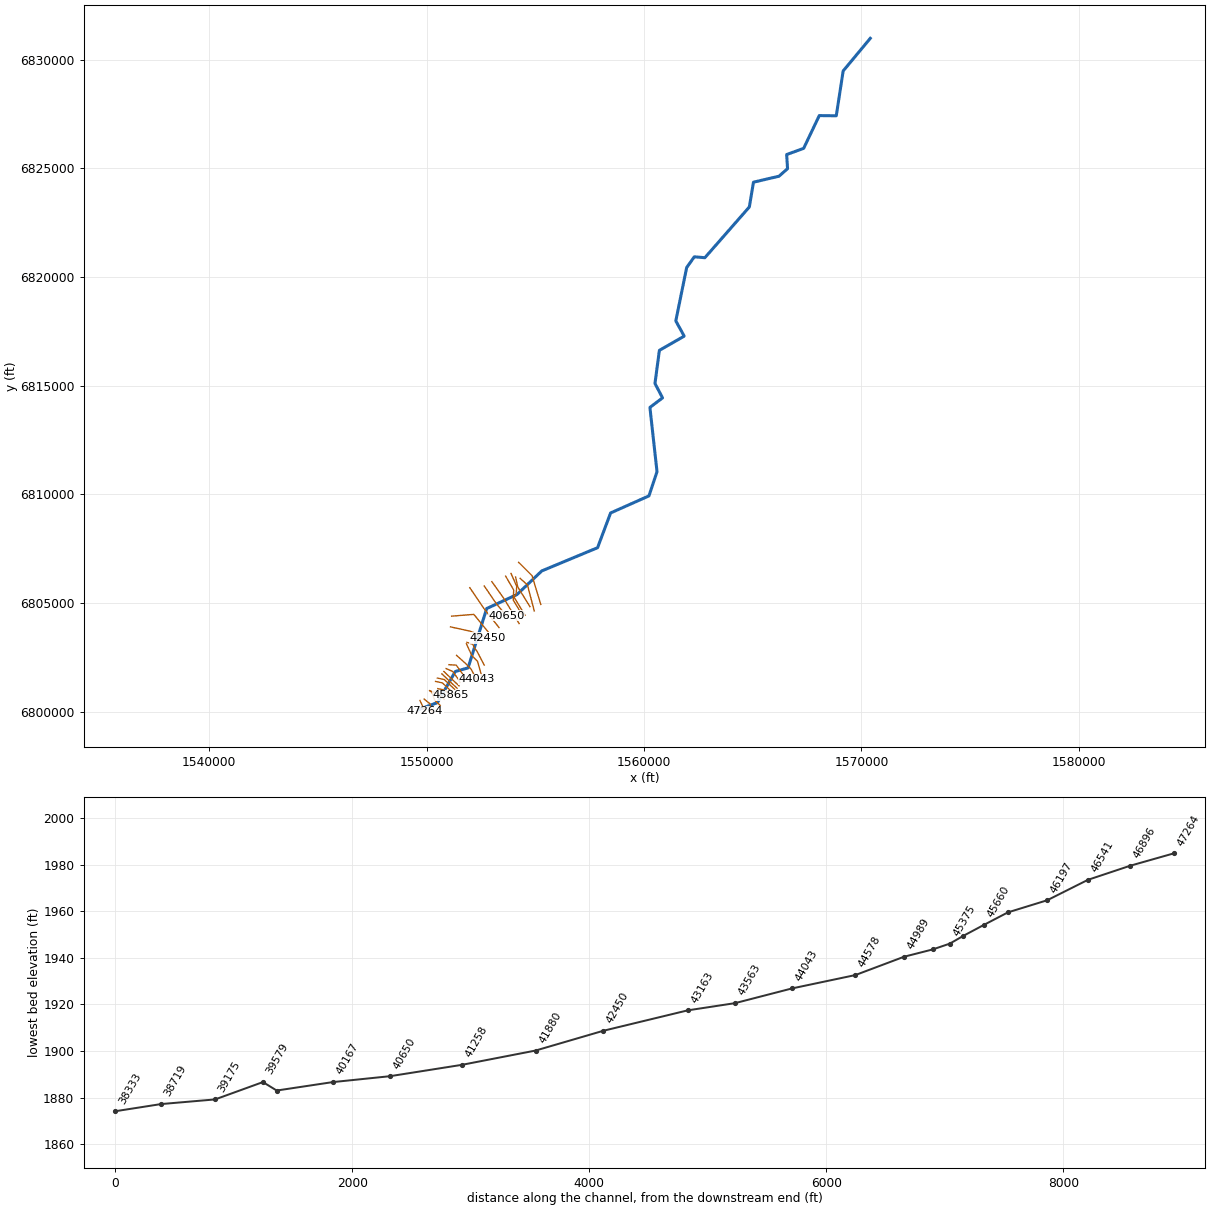
--- Elm 01 17.prj (project) ---

Proj Title=Elm 01 17 Base Level Engineering
Current Plan=p01
Default Exp/Contr=0.3,0.1
English Units
Geom File=g01
Flow File=f01
Plan File=p01
Y Axis Title=Elevation
X Axis Title(PF)=Main Channel Distance
X Axis Title(XS)=Station
BEGIN DESCRIPTION:
Elm 01 17
END DESCRIPTION:
DSS Export Rating Curves= 0
DSS Export Rating Curve Sorted= 0
DSS Export Volume Flow Curves= 0
DXF OffsetX= 0
DXF OffsetY= 0
DXF ScaleX= 1
DXF ScaleY= 10

--- Elm 01 17.p01 (plan) ---

Plan Title=Multiple Run
Program Version=4.10
Short Identifier=Multiple
Geom File=g01
Flow File=f01
Subcritical Flow
K Sum by GR= 0
Std Step Tol= 0.01
Critical Tol= 0.01
Num of Std Step Trials= 20
Max Error Tol= 0.3
Flow Tol Ratio= 0.001
Split Flow NTrial= 30
Split Flow Tol= 0.02
Split Flow Ratio= 0.02
Log Output Level= 0
Friction Slope Method= 1
Unsteady Friction Slope Method= 2
Unsteady Bridges Friction Slope Method= 1
Parabolic Critical Depth
Global Vel Dist= 1 , 1 , 1
Global Log Level= 0
CheckData=True
Encroach Param=-1 ,0,0, 0
BEGIN DESCRIPTION:
Multiple Run
END DESCRIPTION:
Computation Interval=1HOUR
Output Interval=1HOUR
Run HTab= 0
Run UNet= 0
Run PostProcess= 0
Run WQNet= 0
UNET Theta= 1
UNET Theta Warmup= 1
UNET ZTol= 0.02
UNET ZSATol= 0.05
UNET MxIter= 20
UNET MaxInSteps= 0
UNET DtIC= 0
UNET DtMin= 0
UNET MaxCRTS= 20
UNET WFStab= 2
UNET SFStab= 1
UNET WFX= 1
UNET SFX= 1
UNET DSS MLevel= 4
UNET DZMax Abort= 100
UNET Convert EG Bridges= 0
UNET Use Existing IB Tables=-1
UNET Froude Reduction=False
UNET Froude Limit= 1
UNET Froude Power= 10
UNET Time Slicing=0,0, 5
UNET Junction Losses=0
Instantaneous Interval=1HOUR
Write IC File= 0
Write IC File at Sim End=0
Echo Input=False
Echo Parameters=False
Echo Output=False
Write Detailed= 0
WQ AD Non Conservative
WQ ULTIMATE=-1
WQ Max Comp Step=1HOUR
WQ Output Interval=15MIN
WQ Output Selected Increments= 0
WQ Output face flow=0
WQ Output face velocity=0
WQ Output face area=0
WQ Output face dispersion=0
WQ Output cell volume=0
WQ Output cell surface area=0
WQ Output cell continuity=0
WQ Output cumulative cell continuity=0
WQ Output face conc=0
WQ Output face dconc_dx=0
WQ Output face courant=0
WQ Output face peclet=0
WQ Output face adv mass=0
WQ Output face disp mass=0
WQ Output cell mass=0
WQ Output cell source sink temp=0
WQ Output cell source sink nsm=0
WQ Output MaxMinRange=-1
WQ Daily Max Min Mean=-1
WQ Daily Range=0
WQ Daily Time=0
WQ Create Restart=0
WQ Fixed Restart=0
WQ System Summary=0
WQ Use Fixed Temperature=0
Sorting and Armoring Iterations= 10
XS Update Threshold= 0.02
Hydraulics Update Threshold= 0.02
Energy Slope Method= 1
Volume Change Method= 0
XS Weighting Method= 0
Number of US Weighted Cross Sections= 1
Number of DS Weighted Cross Sections= 1
Upstream XS Weight=0.25
Main XS Weight=0.5
Downstream XS Weight=0.25
Number of DS XS's Weighted with US Boundary= 1
Upstream Boundary Weight= 1
Weight of XSs Associated with US Boundary= 0
Number of US XS's Weighted with DS Boundary= 1
Downstream Boundary Weight= 0.5
Weight of XSs Associated with DS Boundary= 0.5
Sediment Output Level= 4
Mass or Volume Output= 0
Output Increment Type= 1
Profile and TS Output Increment= 10
XS Output Flag= 0
XS Output Increment= 10
Disregard all LS=0
Disregard all Conn=0
Disregard all Breaches=0
Disregard all Pumps=0

--- Elm 01 17.f01 (steady flow) ---

Flow Title=Multiple
Number of Profiles=7
Profile Names=10-year,25-year,50-year,1pct_min,100-year,1pct_plu,500-year
River Rch & RM= Elm 01 17,Reach-1,47264
     260     368     460     287     574    1144     902
River Rch & RM= Elm 01 17,Reach-1,44043
     357     515     652     411     821    1637    1319
River Rch & RM= Elm 01 17,Reach-1,41258
     472     685     870     550    1097    2189    1768
River Rch & RM= Elm 01 17,Reach-1,32272
     510     737     931     585    1168    2330    1863
River Rch & RM= Elm 01 17,Reach-1,26072
     519     749     945     593    1184    2363    1883
River Rch & RM= Elm 01 17,Reach-1,21629
     457     644     800     493     984    1963    1510
River Rch & RM= Elm 01 17,Reach-1,15945
     519     735     916     566    1130    2254    1743
River Rch & RM= Elm 01 17,Reach-1,9052
     534     753     937     578    1153    2301    1771
River Rch & RM= Elm 01 17,Reach-1,6509
     566     801     997     616    1228    2451    1890
Boundary for River Rch & Prof#=Elm 01 17,Reach-1,1
Up Type=0
Dn Type=3
Dn Slope=0.005
Boundary for River Rch & Prof#=Elm 01 17,Reach-1,2
Up Type=0
Dn Type=3
Dn Slope=0.005
Boundary for River Rch & Prof#=Elm 01 17,Reach-1,3
Up Type=0
Dn Type=3
Dn Slope=0.005
Boundary for River Rch & Prof#=Elm 01 17,Reach-1,4
Up Type=0
Dn Type=3
Dn Slope=0.005
Boundary for River Rch & Prof#=Elm 01 17,Reach-1,5
Up Type=0
Dn Type=3
Dn Slope=0.005
Boundary for River Rch & Prof#=Elm 01 17,Reach-1,6
Up Type=0
Dn Type=3
Dn Slope=0.005
Boundary for River Rch & Prof#=Elm 01 17,Reach-1,7
Up Type=0
Dn Type=3
Dn Slope=0.005

--- Elm 01 17.g01 (geometry) ---

Geom Title=Existing Conditions

River Reach=Elm 01 17,Reach-1
Reach XY= 30
      1549639.92      6800101.92      1550505.32      6800423.28
      1551322.59      6801852.44      1551910.13      6802019.44
      1552766.79      6804748.90      1554161.21      6805395.86
      1555302.45      6806482.27      1557865.11      6807548.65
      1558465.38      6809148.22      1560227.75      6809933.65
      1560598.53      6811045.39      1560272.61      6814005.55
      1560853.11      6814443.71      1560504.89      6815108.10
      1560708.06      6816629.72      1561848.06      6817284.67
      1561462.77      6817984.59      1561962.60      6820441.33
      1562315.48      6820936.15      1562799.56      6820893.18
      1564844.24      6823228.32      1565034.34      6824368.60
      1566207.30      6824643.09      1566601.47      6824989.45
      1566560.46      6825640.45      1567341.39      6825924.75
      1568060.26      6827432.53      1568841.63      6827423.84
      1569158.53      6829486.55      1570405.00      6830988.00

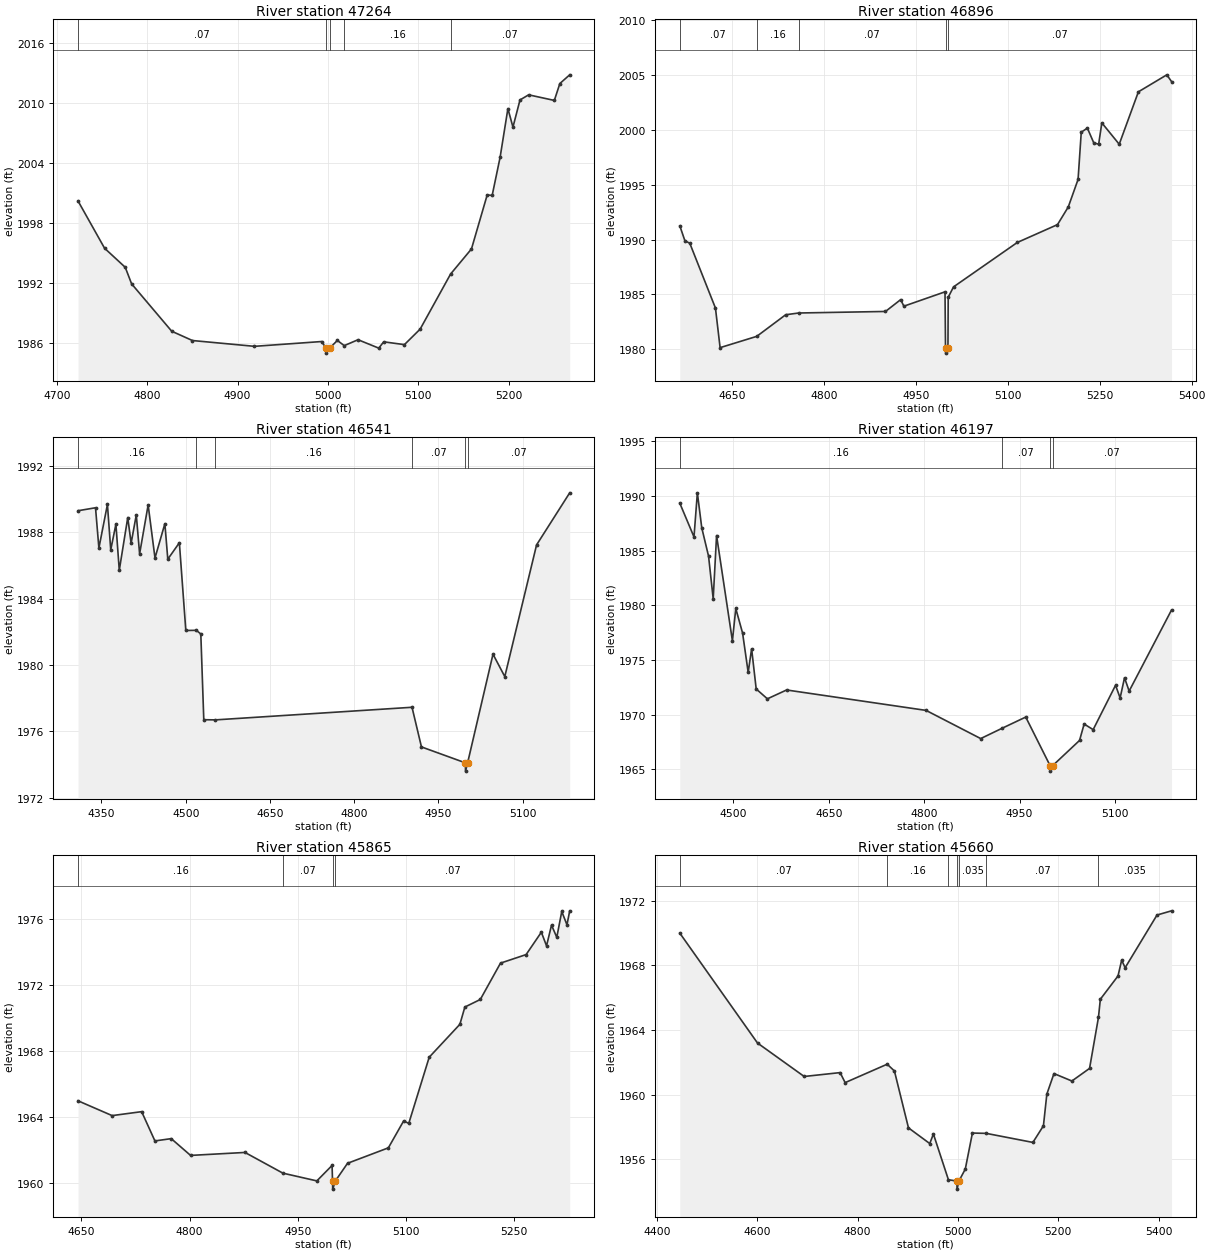
Type RM Length L Ch R = 1,47264,368,368,368
BEGIN DESCRIPTION:
Elm 01 14 45.0
END DESCRIPTION:
XS GIS Cut Line= 2
      1549698.58      6800521.77      1549927.43      6800028.14
#Sta/Elev= 30
  4723.5 2000.18  4752.9 1995.45  4775.8 1993.54  4782.8 1991.89  4827.2 1987.15
  4850.1 1986.22  4918.8 1985.64  4993.1 1986.12  4998.0 1985.46  4998.3 1984.96
  5002.0 1985.46  5010.5 1986.23  5018.1 1985.71  5033.4 1986.30  5056.3 1985.46
  5061.8 1986.09  5084.7 1985.81  5102.1 1987.36  5135.8 1992.87  5158.9 1995.38
  5176.3 2000.78  5181.8 2000.73  5190.6 2004.55  5199.2 2009.41  5204.8 2007.56
  5212.6 2010.28  5222.2 2010.79  5250.6 2010.23  5256.7 2011.92  5267.6 2012.79
#Mann=5,-1,0
  4723.5    0.07       0  4998.0    0.07       0  5002.0    0.07       0
  5018.1    0.16       0  5135.8    0.07       0
Bank Sta=4998,5002
Exp/Cntr=0.3,0.1

Type RM Length L Ch R = 1,46896,355,355,355
BEGIN DESCRIPTION:
Elm 01 14 44.0
END DESCRIPTION:
XS GIS Cut Line= 3
      1549889.82      6800585.24      1550153.60      6800370.82
      1550282.27      6799925.99
#Sta/Elev= 30
  4564.1 1991.25  4572.4 1989.89  4580.4 1989.66  4622.3 1983.75  4629.9 1980.14
  4689.8 1981.17  4737.0 1983.14  4758.4 1983.30  4900.0 1983.44  4924.8 1984.52
  4930.0 1983.92  4997.2 1985.23  4998.0 1980.14  4998.3 1979.64  5002.0 1980.14
  5002.4 1984.73  5011.1 1985.68  5115.2 1989.73  5180.9 1991.36  5198.5 1992.97
  5214.5 1995.48  5219.7 1999.79  5229.7 2000.16  5240.1 1998.82  5248.1 1998.69
  5253.3 2000.64  5281.7 1998.69  5313.0 2003.47  5359.4 2005.02  5367.1 2004.41
#Mann=5,-1,0
  4564.1    0.07       0  4689.8    0.16       0  4758.4    0.07       0
  4998.0    0.07       0  5002.0    0.07       0
Bank Sta=4998,5002
Exp/Cntr=0.3,0.1

Type RM Length L Ch R = 1,46541,344,344,344
BEGIN DESCRIPTION:
Elm 01 14 43.0
END DESCRIPTION:
XS GIS Cut Line= 4
      1550137.65      6800972.50      1550255.44      6800896.12
      1550371.84      6800536.09      1550630.03      6800289.78
#Sta/Elev= 30
  4308.2 1989.31  4339.4 1989.49  4345.4 1987.06  4360.6 1989.69  4366.5 1986.95
  4375.7 1988.50  4381.7 1985.72  4396.8 1988.90  4402.8 1987.35  4412.0 1989.06
  4417.9 1986.71  4433.1 1989.66  4445.3 1986.46  4462.9 1988.53  4468.1 1986.39
  4488.7 1987.38  4500.2 1982.09  4518.9 1982.10  4526.9 1981.88  4532.2 1976.71
  4553.0 1976.70  4903.0 1977.46  4919.8 1975.07  4998.0 1974.11  4998.3 1973.61
  5002.0 1974.11  5047.2 1980.66  5068.2 1979.31  5124.8 1987.25  5183.8 1990.39
#Mann=6,-1,0
  4308.2    0.16       0  4518.9   0.033       0  4553.0    0.16       0
  4903.0    0.07       0  4998.0    0.07       0  5002.0    0.07       0
Bank Sta=4998,5002
Exp/Cntr=0.3,0.1

Type RM Length L Ch R = 1,46197,332,332,332
BEGIN DESCRIPTION:
Elm 01 14 42.0
END DESCRIPTION:
XS GIS Cut Line= 3
      1550172.67      6800962.19      1550562.90      6800814.99
      1550820.51      6800569.23
#Sta/Elev= 30
  4415.8 1989.35  4438.1 1986.26  4443.4 1990.30  4450.3 1987.10  4461.0 1984.50
  4468.3 1980.60  4473.6 1986.39  4498.5 1976.75  4503.8 1979.71  4514.5 1977.46
  4523.3 1973.86  4528.7 1976.02  4535.9 1972.34  4553.5 1971.44  4583.7 1972.25
  4803.0 1970.38  4888.9 1967.80  4922.0 1968.73  4959.7 1969.77  4998.0 1965.32
  4998.3 1964.82  5002.0 1965.32  5044.3 1967.63  5051.5 1969.13  5065.7 1968.62
  5100.9 1972.68  5108.1 1971.52  5115.0 1973.37  5122.3 1972.15  5188.9 1979.57
#Mann=4,-1,0
  4415.8    0.16       0  4922.0    0.07       0  4998.0    0.07       0
  5002.0    0.07       0
Bank Sta=4998,5002
Exp/Cntr=0.3,0.1

Type RM Length L Ch R = 1,45865,205,205,205
BEGIN DESCRIPTION:
Elm 01 14 41.0
END DESCRIPTION:
XS GIS Cut Line= 3
      1550518.73      6801066.03      1550837.25      6800997.59
      1551094.56      6800752.13
#Sta/Elev= 30
  4645.3 1964.97  4692.6 1964.07  4733.5 1964.31  4751.9 1962.53  4774.5 1962.67
  4801.3 1961.65  4876.7 1961.83  4929.3 1960.57  4976.3 1960.10  4997.4 1961.04
  4998.0 1960.10  4998.3 1959.60  5002.0 1960.10  5018.8 1961.17  5075.4 1962.11
  5096.5 1963.74  5103.7 1963.60  5132.0 1967.62  5174.5 1969.62  5181.4 1970.67
  5202.8 1971.13  5230.8 1973.34  5266.3 1973.86  5287.4 1975.22  5294.6 1974.39
  5301.5 1975.65  5308.8 1974.91  5315.7 1976.48  5322.9 1975.67  5326.7 1976.52
#Mann=4,-1,0
  4645.3    0.16       0  4929.3    0.07       0  4998.0    0.07       0
  5002.0    0.07       0
Bank Sta=4998,5002
Exp/Cntr=0.3,0.1

Type RM Length L Ch R = 1,45660,172,172,172
BEGIN DESCRIPTION:
Elm 01 14 40.0
END DESCRIPTION:
XS GIS Cut Line= 4
      1550412.70      6801396.38      1550731.23      6801327.93
      1550989.42      6801081.62      1551207.34      6800879.73
#Sta/Elev= 30
  4445.9 1969.99  4600.7 1963.19  4693.7 1961.12  4765.3 1961.36  4775.3 1960.74
  4859.1 1961.88  4873.5 1961.46  4901.5 1957.94  4943.9 1956.97  4951.2 1957.56
  4981.1 1954.73  4998.0 1954.65  4998.3 1954.15  5002.0 1954.65  5014.7 1955.39
  5028.9 1957.62  5056.5 1957.60  5149.4 1957.04  5170.4 1958.07  5177.2 1960.03
  5191.4 1961.30  5227.1 1960.84  5262.3 1961.62  5280.0 1964.77  5283.8 1965.90
  5319.0 1967.34  5326.3 1968.32  5333.2 1967.85  5396.7 1971.11  5425.6 1971.37
#Mann=7,-1,0
  4445.9    0.07       0  4859.1    0.16       0  4981.1   0.035       0
  4998.0   0.035       0  5002.0   0.035       0  5056.5    0.07       0
  5280.0   0.035       0
Bank Sta=4998,5002
Exp/Cntr=0.3,0.1

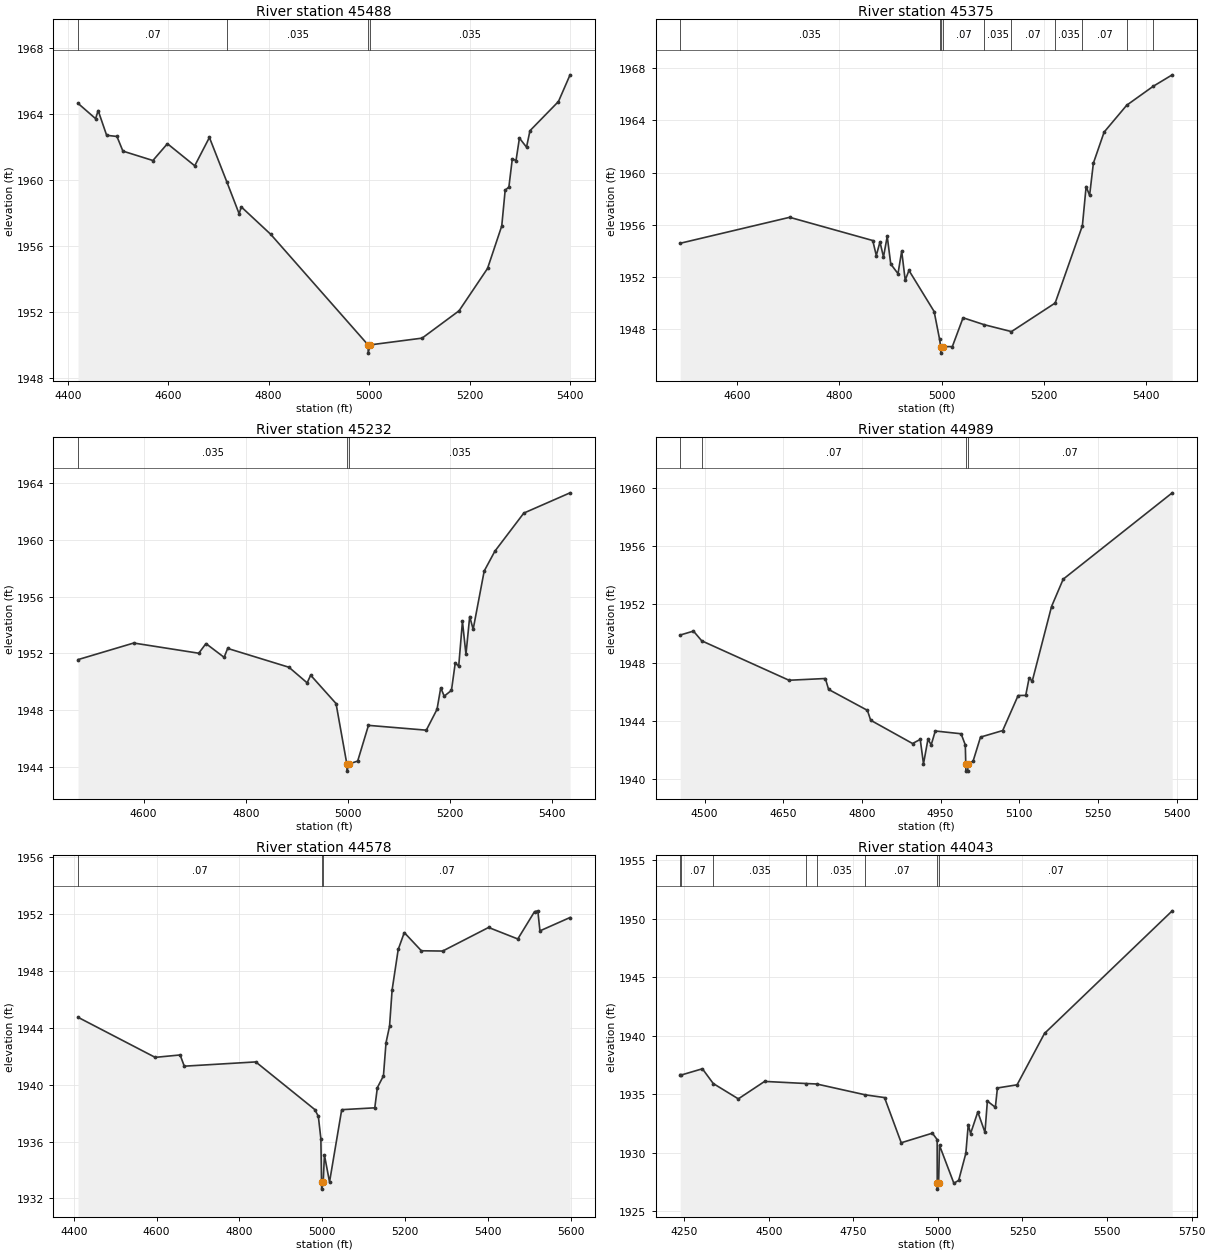
Type RM Length L Ch R = 1,45488,113,113,113
BEGIN DESCRIPTION:
Elm 01 14 39.0
END DESCRIPTION:
XS GIS Cut Line= 4
      1550499.27      6801551.09      1550817.77      6801482.65
      1551075.95      6801236.34      1551293.90      6801034.42
#Sta/Elev= 30
  4420.5 1964.64  4455.5 1963.71  4460.6 1964.20  4477.5 1962.70  4498.0 1962.63
  4509.9 1961.74  4569.6 1961.17  4598.5 1962.19  4652.9 1960.85  4682.1 1962.57
  4717.1 1959.85  4741.4 1957.93  4745.4 1958.36  4804.2 1956.69  4998.0 1949.98
  4998.3 1949.48  5002.0 1949.98  5105.6 1950.39  5179.2 1952.05  5235.9 1954.62
  5264.2 1957.20  5271.0 1959.37  5278.4 1959.56  5285.2 1961.27  5292.6 1961.17
  5299.4 1962.53  5313.5 1961.98  5320.4 1962.98  5377.1 1964.75  5400.2 1966.37
#Mann=4,-1,0
  4420.5    0.07       0  4717.1   0.035       0  4998.0   0.035       0
  5002.0   0.035       0
Bank Sta=4998,5002
Exp/Cntr=0.3,0.1

Type RM Length L Ch R = 1,45375,143,143,143
BEGIN DESCRIPTION:
Elm 01 14 38.0
END DESCRIPTION:
XS GIS Cut Line= 3
      1550707.53      6801743.22      1551190.50      6801282.48
      1551407.12      6801081.78
#Sta/Elev= 30
  4488.3 1954.59  4702.5 1956.58  4865.1 1954.80  4872.0 1953.65  4879.2 1954.69
  4886.1 1953.54  4893.4 1955.12  4900.3 1953.00  4914.5 1952.26  4921.7 1953.99
  4928.6 1951.76  4935.9 1952.51  4985.2 1949.36  4995.9 1947.22  4998.0 1946.67
  4998.3 1946.17  5002.0 1946.67  5020.8 1946.67  5041.8 1948.88  5083.1 1948.35
  5136.5 1947.82  5222.0 1950.01  5275.3 1955.94  5282.6 1958.94  5289.4 1958.26
  5296.8 1960.73  5317.8 1963.11  5362.0 1965.17  5413.8 1966.62  5451.1 1967.50
#Mann=10,-1,0
  4488.3   0.035       0  4995.9    0.07       0  4998.0    0.07       0
  5002.0    0.07       0  5083.1   0.035       0  5136.5    0.07       0
  5222.0   0.035       0  5275.3    0.07       0  5362.0   0.035       0
  5413.8    0.07       0
Bank Sta=4998,5002
Exp/Cntr=0.3,0.1

Type RM Length L Ch R = 1,45232,243,243,243
BEGIN DESCRIPTION:
Elm 01 14 37.0
END DESCRIPTION:
XS GIS Cut Line= 3
      1550797.20      6801854.60      1551280.14      6801393.87
      1551497.53      6801192.47
#Sta/Elev= 30
  4471.4 1951.56  4580.5 1952.73  4707.9 1952.01  4722.0 1952.69  4757.6 1951.72
  4764.5 1952.35  4884.6 1951.02  4920.2 1949.92  4927.1 1950.46  4976.8 1948.46
  4998.0 1944.19  4998.3 1943.69  5002.0 1944.19  5019.2 1944.40  5040.3 1946.92
  5153.6 1946.58  5174.6 1948.05  5181.9 1949.57  5188.7 1948.98  5202.9 1949.39
  5210.3 1951.32  5217.1 1951.10  5224.4 1954.25  5231.3 1951.93  5238.6 1954.60
  5245.4 1953.70  5267.0 1957.81  5287.9 1959.21  5344.6 1961.90  5435.2 1963.33
#Mann=3,-1,0
  4471.4   0.035       0  4998.0   0.035       0  5002.0   0.035       0
Bank Sta=4998,5002
Exp/Cntr=0.3,0.1

Type RM Length L Ch R = 1,44989,411,411,411
BEGIN DESCRIPTION:
Elm 01 14 36.0
END DESCRIPTION:
XS GIS Cut Line= 4
      1550901.85      6801987.42      1551205.19      6801853.67
      1551494.08      6801451.72      1551533.17      6801347.32
#Sta/Elev= 30
  4453.6 1949.89  4478.9 1950.16  4494.7 1949.49  4661.0 1946.78  4730.3 1946.90
  4736.5 1946.15  4810.5 1944.71  4816.7 1944.03  4896.5 1942.43  4911.2 1942.71
  4917.4 1941.03  4925.9 1942.72  4932.1 1942.34  4939.9 1943.29  4989.1 1943.10
  4997.1 1942.33  4998.0 1941.03  4998.3 1940.53  5001.8 1940.53  5002.0 1941.03
  5011.9 1941.21  5026.1 1942.87  5068.4 1943.32  5097.8 1945.73  5112.3 1945.74
  5118.7 1946.92  5124.8 1946.73  5161.5 1951.85  5183.7 1953.73  5391.6 1959.67
#Mann=4,-1,0
  4453.6   0.035       0  4494.7    0.07       0  4998.0    0.07       0
  5002.0    0.07       0
Bank Sta=4998,5002
Exp/Cntr=0.3,0.1

Type RM Length L Ch R = 1,44578,535,535,535
BEGIN DESCRIPTION:
Elm 01 14 35.0
END DESCRIPTION:
XS GIS Cut Line= 4
      1551029.15      6802167.59      1551367.00      6802145.93
      1551655.89      6801743.99      1551699.15      6801392.88
#Sta/Elev= 30
  4410.4 1944.74  4596.6 1941.92  4656.8 1942.09  4666.8 1941.30  4839.3 1941.60
  4981.7 1938.25  4990.3 1937.77  4996.4 1936.20  4998.0 1933.15  4998.3 1932.65
  5002.0 1933.15  5005.0 1935.05  5017.3 1933.15  5046.7 1938.24  5126.5 1938.37
  5132.7 1939.79  5147.4 1940.62  5153.6 1942.95  5162.1 1944.11  5168.3 1946.66
  5183.0 1949.51  5197.7 1950.70  5238.9 1949.42  5290.3 1949.40  5401.1 1951.06
  5471.6 1950.25  5511.9 1952.17  5519.9 1952.23  5525.0 1950.82  5597.7 1951.76
#Mann=3,-1,0
  4410.4    0.07       0  4998.0    0.07       0  5002.0    0.07       0
Bank Sta=4998,5002
Exp/Cntr=0.3,0.1

Type RM Length L Ch R = 1,44043,480,480,480
BEGIN DESCRIPTION:
Elm 01 14 34.0
END DESCRIPTION:
XS GIS Cut Line= 4
      1551380.15      6802595.93      1551787.12      6802231.44
      1552055.57      6801955.29      1552292.20      6801489.06
#Sta/Elev= 30
  4238.3 1936.68  4241.8 1936.65  4303.9 1937.18  4336.0 1935.92  4410.1 1934.61
  4487.8 1936.10  4610.4 1935.92  4641.6 1935.88  4785.9 1934.95  4842.2 1934.72
  4891.6 1930.86  4983.7 1931.68  4997.8 1931.13  4998.0 1927.40  4998.3 1926.90
  5002.0 1927.40  5004.8 1930.63  5047.2 1927.40  5061.4 1927.65  5082.5 1929.95
  5089.7 1932.41  5096.6 1931.65  5117.9 1933.49  5139.1 1931.75  5146.2 1934.42
  5169.8 1933.89  5175.9 1935.54  5234.0 1935.81  5315.1 1940.20  5692.6 1950.67
#Mann=8,-1,0
  4238.3   0.035       0  4241.8    0.07       0  4336.0   0.035       0
  4610.4    0.07       0  4641.6   0.035       0  4785.9    0.07       0
  4998.0    0.07       0  5002.0    0.07       0
Bank Sta=4998,5002
Exp/Cntr=0.3,0.1

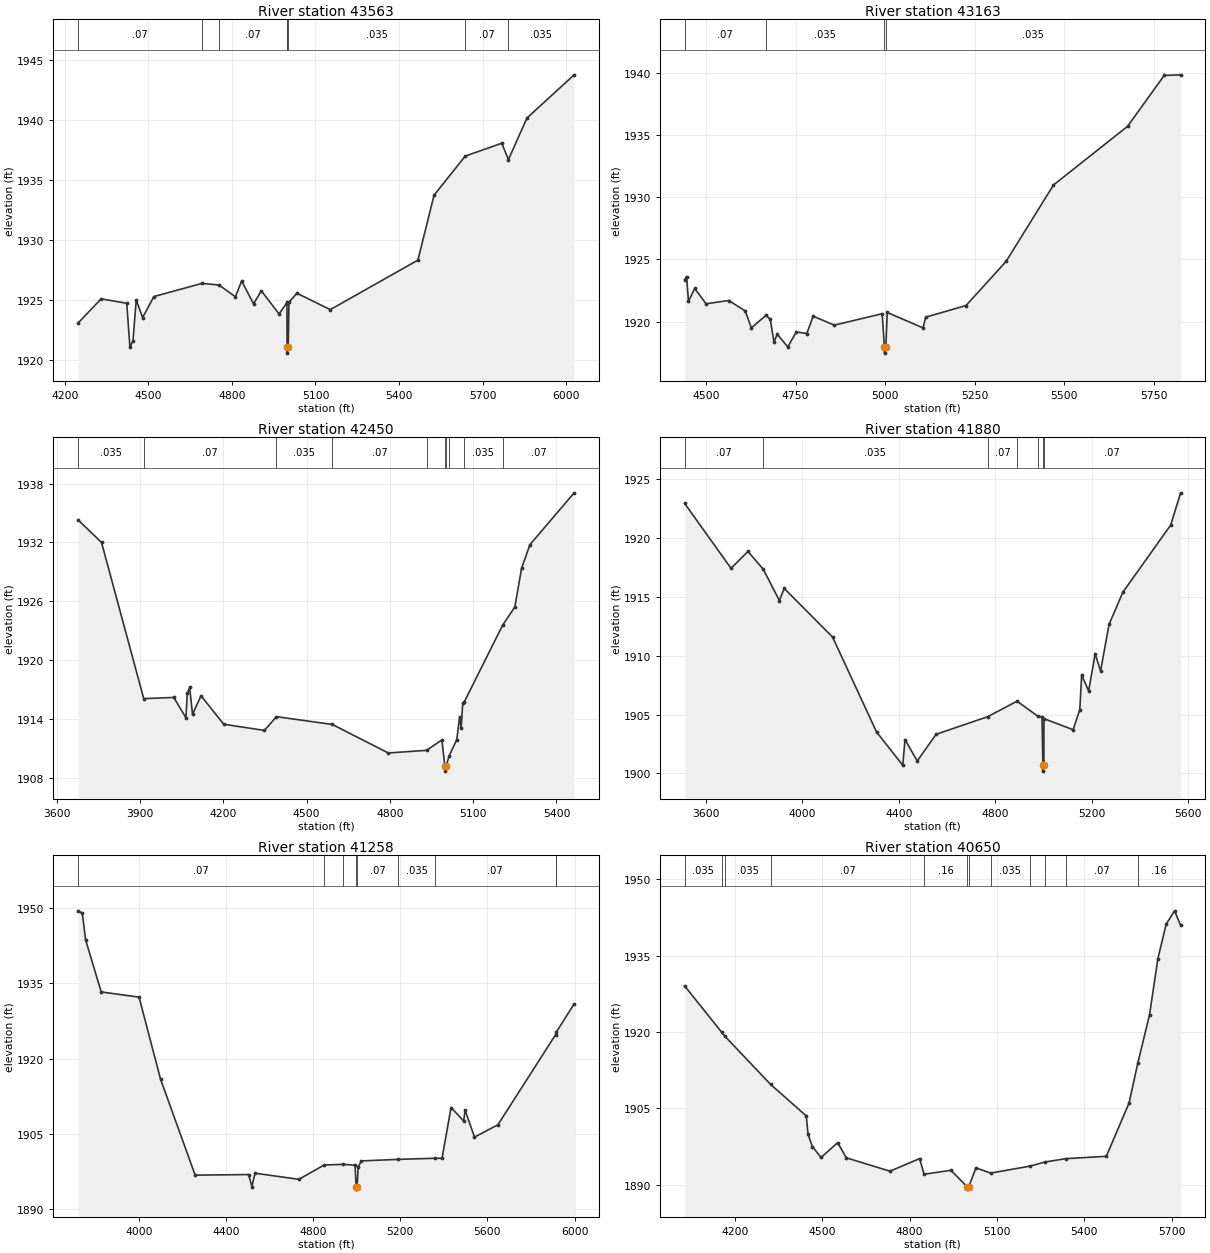
Type RM Length L Ch R = 1,43563,400,400,400
BEGIN DESCRIPTION:
Elm 01 14 33.0
END DESCRIPTION:
XS GIS Cut Line= 4
      1551835.36      6803126.87      1552078.49      6802595.63
      1552346.94      6802319.48      1552564.81      6801537.52
#Sta/Elev= 30
  4247.9 1923.10  4330.1 1925.11  4422.2 1924.74  4433.6 1921.08  4444.6 1921.62
  4456.2 1925.01  4479.2 1923.55  4519.7 1925.30  4692.6 1926.40  4753.9 1926.26
  4812.4 1925.28  4835.0 1926.60  4877.5 1924.70  4905.8 1925.77  4969.3 1923.85
  4996.6 1924.76  4997.6 1924.86  4998.0 1921.08  4998.3 1920.58  5002.0 1921.08
  5004.8 1924.82  5033.1 1925.58  5153.2 1924.21  5467.9 1928.34  5525.9 1933.76
  5637.9 1937.02  5769.0 1938.09  5793.0 1936.73  5859.6 1940.20  6029.0 1943.80
#Mann=8,-1,0
  4247.9    0.07       0  4692.6   0.035       0  4753.9    0.07       0
  4996.6   0.035       0  4998.0   0.035       0  5002.0   0.035       0
  5637.9    0.07       0  5793.0   0.035       0
Bank Sta=4998,5002
Exp/Cntr=0.3,0.1

Type RM Length L Ch R = 1,43163,713,713,713
BEGIN DESCRIPTION:
Elm 01 14 32.0
END DESCRIPTION:
XS GIS Cut Line= 5
      1551858.34      6803195.80      1552129.14      6803105.76
      1552211.51      6802907.94      1552305.28      6802814.06
      1552653.50      6802146.69
#Sta/Elev= 30
  4440.2 1923.39  4445.5 1923.63  4450.8 1921.64  4468.3 1922.67  4499.9 1921.44
  4563.1 1921.70  4609.1 1920.87  4626.4 1919.50  4667.1 1920.50  4679.1 1920.21
  4689.6 1918.37  4698.7 1918.99  4728.2 1917.97  4752.0 1919.18  4781.3 1919.04
  4799.0 1920.44  4858.2 1919.72  4991.8 1920.64  4998.0 1917.97  4998.3 1917.47
  5002.0 1917.97  5005.9 1920.74  5106.0 1919.50  5113.2 1920.36  5226.0 1921.30
  5337.7 1924.84  5470.2 1930.99  5677.2 1935.71  5779.4 1939.80  5825.3 1939.85
#Mann=4,-1,0
  4440.2    0.07       0  4667.1   0.035       0  4998.0   0.035       0
  5002.0   0.035       0
Bank Sta=4998,5002
Exp/Cntr=0.3,0.1

Type RM Length L Ch R = 1,42450,570,570,570
BEGIN DESCRIPTION:
Elm 01 14 31.0
END DESCRIPTION:
XS GIS Cut Line= 3
      1551102.95      6803906.75      1552000.89      6803709.08
      1552809.13      6803395.72
#Sta/Elev= 30
  3677.3 1934.28  3761.3 1931.99  3913.3 1916.07  4021.4 1916.19  4065.1 1914.13
  4070.2 1916.60  4078.7 1917.21  4089.0 1914.48  4119.7 1916.36  4201.4 1913.46
  4348.0 1912.83  4391.4 1914.23  4592.5 1913.44  4794.2 1910.53  4932.0 1910.80
  4987.3 1911.86  4998.0 1909.18  4998.2 1908.68  5002.1 1909.18  5013.1 1910.22
  5040.9 1911.90  5051.2 1914.24  5056.6 1913.09  5062.3 1915.59  5067.5 1915.72
  5205.8 1923.55  5249.9 1925.41  5274.5 1929.39  5304.4 1931.77  5463.6 1937.05
#Mann=10,-1,0
  3677.3   0.035       0  3913.3    0.07       0  4391.4   0.035       0
  4592.5    0.07       0  4932.0   0.035       0  4998.0   0.035       0
  5002.1   0.035       0  5013.1    0.07       0  5067.5   0.035       0
  5205.8    0.07       0
Bank Sta=4998,5002.1
Exp/Cntr=0.3,0.1

Type RM Length L Ch R = 1,41880,622,622,622
BEGIN DESCRIPTION:
Elm 01 14 30.0
END DESCRIPTION:
XS GIS Cut Line= 3
      1551153.43      6804399.57      1552176.20      6804481.66
      1552826.79      6803682.05
#Sta/Elev= 30
  3512.3 1922.89  3704.5 1917.39  3774.7 1918.82  3838.3 1917.31  3905.1 1914.66
  3925.2 1915.69  4125.8 1911.56  4308.3 1903.51  4416.8 1900.70  4426.0 1902.87
  4477.0 1901.06  4554.9 1903.32  4768.6 1904.81  4890.9 1906.13  4977.2 1904.85
  4994.4 1904.81  4998.0 1900.70  4998.2 1900.20  5002.1 1900.70  5002.3 1904.65
  5123.2 1903.71  5151.0 1905.41  5158.9 1908.35  5187.6 1907.00  5214.9 1910.14
  5237.2 1908.69  5272.3 1912.63  5329.5 1915.36  5528.0 1921.06  5569.2 1923.79
#Mann=7,-1,0
  3512.3    0.07       0  3838.3   0.035       0  4768.6    0.07       0
  4890.9   0.035       0  4977.2    0.07       0  4998.0    0.07       0
  5002.1    0.07       0
Bank Sta=4998,5002.1
Exp/Cntr=0.3,0.1

Type RM Length L Ch R = 1,41258,608,608,608
BEGIN DESCRIPTION:
Elm 01 14 29.0
END DESCRIPTION:
XS GIS Cut Line= 3
      1551989.79      6805709.08      1552651.16      6804735.61
      1553333.50      6803873.82
#Sta/Elev= 30
  3722.3 1949.42  3741.1 1948.98  3756.0 1943.67  3827.9 1933.28  4001.5 1932.25
  4100.4 1915.89  4259.1 1896.83  4504.5 1896.95  4519.5 1894.55  4533.6 1897.22
  4735.0 1896.00  4851.0 1898.85  4938.1 1898.98  4992.9 1898.81  4997.9 1894.55
  4998.2 1894.05  5002.2 1894.55  5007.3 1898.47  5021.8 1899.66  5190.8 1899.97
  5359.6 1900.19  5392.0 1900.19  5433.6 1910.29  5491.3 1907.60  5497.7 1909.76
  5541.0 1904.40  5648.4 1906.85  5912.8 1924.75  5915.8 1925.24  5998.4 1930.91
#Mann=9,-1,0
  3722.3    0.07       0  4851.0   0.035       0  4938.1    0.07       0
  4997.9    0.07       0  5002.2    0.07       0  5190.8   0.035       0
  5359.6    0.07       0  5912.8   0.035       0  5915.8    0.07       0
Bank Sta=4997.9,5002.2
Exp/Cntr=0.3,0.1

Type RM Length L Ch R = 1,40650,483,483,483
BEGIN DESCRIPTION:
Elm 01 14 28.0
END DESCRIPTION:
XS GIS Cut Line= 3
      1552654.98      6805788.04      1553201.97      6804983.95
      1553669.81      6804422.79
#Sta/Elev= 30
  4027.5 1929.03  4154.9 1919.93  4165.9 1919.15  4322.6 1909.71  4445.1 1903.53
  4451.1 1899.92  4466.1 1897.51  4495.9 1895.37  4552.8 1898.29  4582.7 1895.30
  4732.4 1892.68  4834.2 1895.15  4849.6 1892.08  4941.9 1892.86  4996.8 1889.66
  4997.3 1889.16  5003.2 1889.66  5027.7 1893.34  5078.3 1892.31  5212.8 1893.67
  5263.8 1894.47  5336.4 1895.14  5475.5 1895.60  5553.6 1906.08  5584.0 1914.00
  5623.9 1923.39  5652.5 1934.41  5681.1 1941.18  5709.8 1943.78  5730.6 1940.93
#Mann=12,-1,0
  4027.5   0.035       0  4154.9    0.07       0  4165.9   0.035       0
  4322.6    0.07       0  4849.6    0.16       0  4996.8    0.07       0
  5003.2    0.16       0  5078.3   0.035       0  5212.8    0.07       0
  5263.8   0.035       0  5336.4    0.07       0  5584.0    0.16       0
Bank Sta=4996.8,5003.2
Exp/Cntr=0.3,0.1

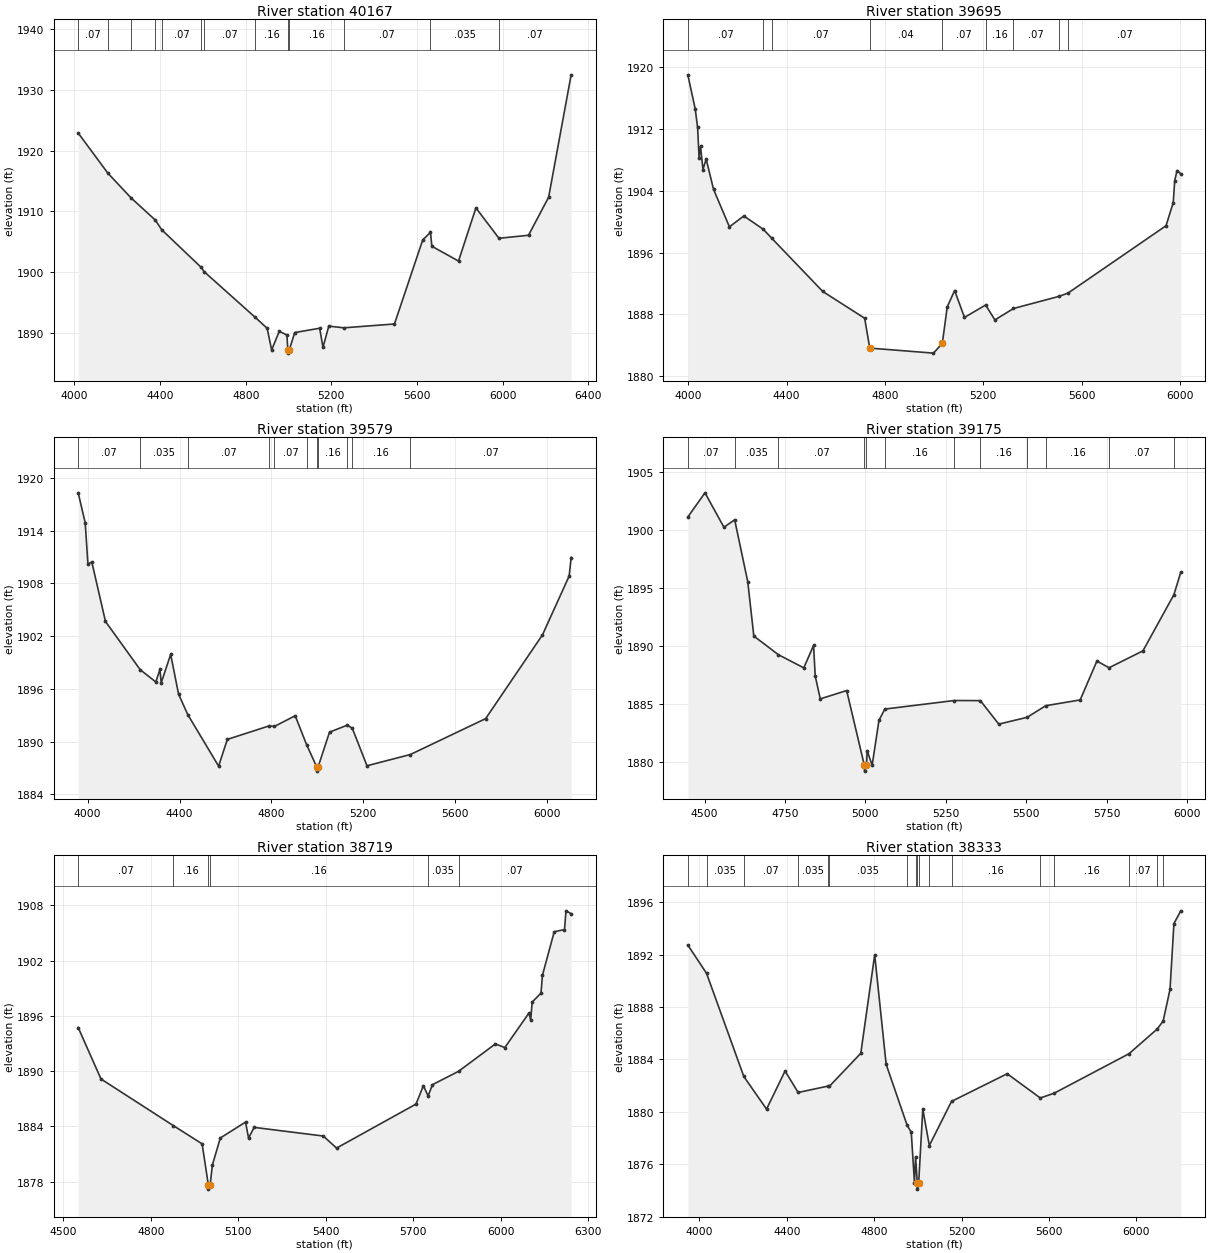
Type RM Length L Ch R = 1,40167,472,472,472
BEGIN DESCRIPTION:
Elm 01 14 27.0
END DESCRIPTION:
XS GIS Cut Line= 3
      1553004.99      6805988.01      1553575.16      6805187.76
      1554257.03      6804057.51
#Sta/Elev= 30
  4017.4 1922.88  4156.1 1916.27  4263.9 1912.21  4378.0 1908.53  4407.1 1906.96
  4591.9 1900.75  4605.1 1900.06  4844.8 1892.50  4900.1 1890.71  4921.0 1887.14
  4956.7 1890.22  4992.3 1889.60  4996.8 1887.12  4997.3 1886.62  5003.3 1887.12
  5028.8 1890.01  5145.3 1890.72  5160.8 1887.57  5188.0 1891.07  5258.1 1890.79
  5494.7 1891.42  5626.7 1905.27  5662.9 1906.52  5669.4 1904.23  5793.9 1901.79
  5875.2 1910.55  5982.9 1905.54  6120.9 1906.04  6214.9 1912.31  6320.0 1932.47
#Mann=13,-1,0
  4017.4    0.07       0  4156.1   0.035       0  4263.9    0.07       0
  4378.0   0.035       0  4407.1    0.07       0  4591.9   0.035       0
  4605.1    0.07       0  4844.8    0.16       0  4996.8    0.07       0
  5003.3    0.16       0  5258.1    0.07       0  5662.9   0.035       0
  5982.9    0.07       0
Bank Sta=4996.8,5003.3
Exp/Cntr=0.3,0.1

Type RM Length L Ch R = 1,39695,116,116,116
BEGIN DESCRIPTION:
Elm 01 14 26.0
END DESCRIPTION:
XS GIS Cut Line= 5
      1553636.81      6806242.44      1554009.16      6805602.52
      1553993.56      6805328.32      1553988.03      6805132.40
      1554406.17      6804457.08
#Sta/Elev= 30
  3997.9 1918.98  4028.0 1914.57  4037.7 1912.18  4043.8 1908.24  4049.6 1909.74
  4059.5 1906.74  4072.5 1908.09  4102.5 1904.18  4167.1 1899.33  4225.8 1900.73
  4305.4 1899.00  4339.4 1897.85  4546.9 1890.97  4717.3 1887.51  4738.0 1883.65
  4997.3 1883.00  5033.2 1884.26  5053.2 1888.98  5083.3 1891.09  5123.3 1887.62
  5209.4 1889.22  5247.1 1887.29  5322.7 1888.77  5508.2 1890.34  5544.9 1890.77
  5943.3 1899.47  5972.6 1902.47  5978.6 1905.29  5988.0 1906.60  6003.2 1906.19
#Mann=9,-1,0
  3997.9    0.07       0  4305.4   0.035       0  4339.4    0.07       0
  4738.0    0.04       0  5033.2    0.07       0  5209.4    0.16       0
  5322.7    0.07       0  5508.2   0.035       0  5544.9    0.07       0
Bank Sta=4738,5033.2
Exp/Cntr=0.3,0.1

Type RM Length L Ch R = 1,39579,404,404,404
BEGIN DESCRIPTION:
Elm 01 14 25.4
END DESCRIPTION:
XS GIS Cut Line= 5
      1553885.79      6806366.71      1554147.48      6805771.80
      1554122.02      6805437.15      1554029.04      6805263.73
      1554532.35      6804442.15
#Sta/Elev= 30
  3958.7 1918.29  3989.3 1914.88  4001.0 1910.21  4018.1 1910.41  4077.5 1903.66
  4228.8 1898.17  4296.7 1896.78  4314.6 1898.21  4320.1 1896.68  4361.3 1899.92
  4395.5 1895.41  4435.5 1893.08  4569.9 1887.21  4608.0 1890.25  4789.3 1891.78
  4812.8 1891.72  4903.3 1892.94  4953.1 1889.64  4996.7 1887.14  4997.2 1886.64
  5003.3 1887.14  5052.7 1891.07  5130.2 1891.87  5151.8 1891.52  5215.8 1887.25
  5404.7 1888.53  5732.3 1892.61  5979.8 1902.14  6095.9 1908.83  6104.5 1910.93
#Mann=11,-1,0
  3958.7    0.07       0  4228.8   0.035       0  4435.5    0.07       0
  4789.3    0.16       0  4812.8    0.07       0  4953.1    0.16       0
  4996.7    0.07       0  5003.3    0.16       0  5130.2    0.07       0
  5151.8    0.16       0  5404.7    0.07       0
Bank Sta=4996.7,5003.3
Exp/Cntr=0.3,0.1

Type RM Length L Ch R = 1,39175,456,456,456
BEGIN DESCRIPTION:
Elm 01 14 25.0
END DESCRIPTION:
XS GIS Cut Line= 3
      1554095.46      6806200.11      1554195.51      6805742.68
      1554754.98      6804838.04
#Sta/Elev= 30
  4448.1 1901.13  4501.4 1903.22  4560.3 1900.25  4593.7 1900.89  4634.5 1895.52
  4653.2 1890.85  4729.4 1889.24  4808.5 1888.10  4838.9 1890.04  4844.0 1887.40
  4859.7 1885.42  4941.7 1886.14  4996.7 1879.68  4997.2 1879.18  5003.3 1879.68
  5005.5 1880.94  5020.9 1879.68  5042.1 1883.56  5060.2 1884.54  5276.2 1885.28
  5357.2 1885.27  5414.5 1883.24  5502.7 1883.83  5560.3 1884.83  5667.4 1885.33
  5719.4 1888.69  5757.1 1888.11  5862.5 1889.57  5958.6 1894.42  5980.0 1896.36
#Mann=12,-1,0
  4448.1    0.07       0  4593.7   0.035       0  4729.4    0.07       0
  4996.7    0.07       0  5003.3    0.07       0  5060.2    0.16       0
  5276.2    0.07       0  5357.2    0.16       0  5502.7    0.07       0
  5560.3    0.16       0  5757.1    0.07       0  5958.6    0.16       0
Bank Sta=4996.7,5003.3
Exp/Cntr=0.3,0.1

Type RM Length L Ch R = 1,38719,386,386,386
BEGIN DESCRIPTION:
Elm 01 14 24.0
END DESCRIPTION:
XS GIS Cut Line= 3
      1554305.03      6806137.98      1554639.96      6805838.35
      1554955.00      6804638.00
#Sta/Elev= 30
  4550.6 1894.74  4628.7 1889.15  4876.9 1884.08  4975.6 1882.10  4996.7 1877.68
  4997.2 1877.18  5003.3 1877.68  5010.7 1879.79  5038.0 1882.74  5124.4 1884.46
  5134.8 1882.73  5154.0 1883.89  5391.1 1882.95  5436.6 1881.64  5708.9 1886.42
  5734.4 1888.42  5750.6 1887.30  5765.4 1888.53  5854.9 1889.98  5981.2 1892.96
  6013.5 1892.56  6096.3 1896.31  6102.3 1895.55  6107.4 1897.51  6137.5 1898.47
  6142.7 1900.43  6183.0 1905.15  6218.2 1905.38  6223.4 1907.42  6241.0 1907.11
#Mann=6,-1,0
  4550.6    0.07       0  4876.9    0.16       0  4996.7    0.07       0
  5003.3    0.16       0  5750.6   0.035       0  5854.9    0.07       0
Bank Sta=4996.7,5003.3
Exp/Cntr=0.3,0.1

Type RM Length L Ch R = 1,38333,420,420,420
BEGIN DESCRIPTION:
Elm 01 14 23.0
END DESCRIPTION:
XS GIS Cut Line= 3
      1554234.63      6806877.11      1554851.27      6806265.09
      1555254.99      6804938.04
#Sta/Elev= 30
  3946.7 1892.74  4032.6 1890.57  4203.0 1882.70  4307.0 1880.21  4391.8 1883.12
  4451.6 1881.48  4589.5 1881.97  4595.0 1881.96  4738.3 1884.47  4801.9 1891.99
  4854.3 1883.63  4950.5 1878.97  4969.2 1878.45  4983.9 1874.60  4989.0 1876.58
  4996.7 1874.60  4997.2 1874.10  5003.3 1874.60  5022.0 1880.21  5052.0 1877.43
  5153.5 1880.80  5408.3 1882.91  5559.7 1881.06  5622.7 1881.42  5965.8 1884.44
  6094.4 1886.32  6121.9 1886.93  6153.4 1889.35  6171.3 1894.38  6202.6 1895.35
#Mann=17,-1,0
  3946.7    0.07       0  4032.6   0.035       0  4203.0    0.07       0
  4451.6   0.035       0  4589.5    0.07       0  4595.0   0.035       0
  4950.5    0.07       0  4989.0    0.16       0  4996.7    0.07       0
  5003.3    0.16       0  5052.0    0.07       0  5153.5    0.16       0
  5559.7    0.07       0  5622.7    0.16       0  5965.8    0.07       0
  6094.4   0.035       0  6121.9    0.07       0
Bank Sta=4996.7,5003.3
Exp/Cntr=0.3,0.1