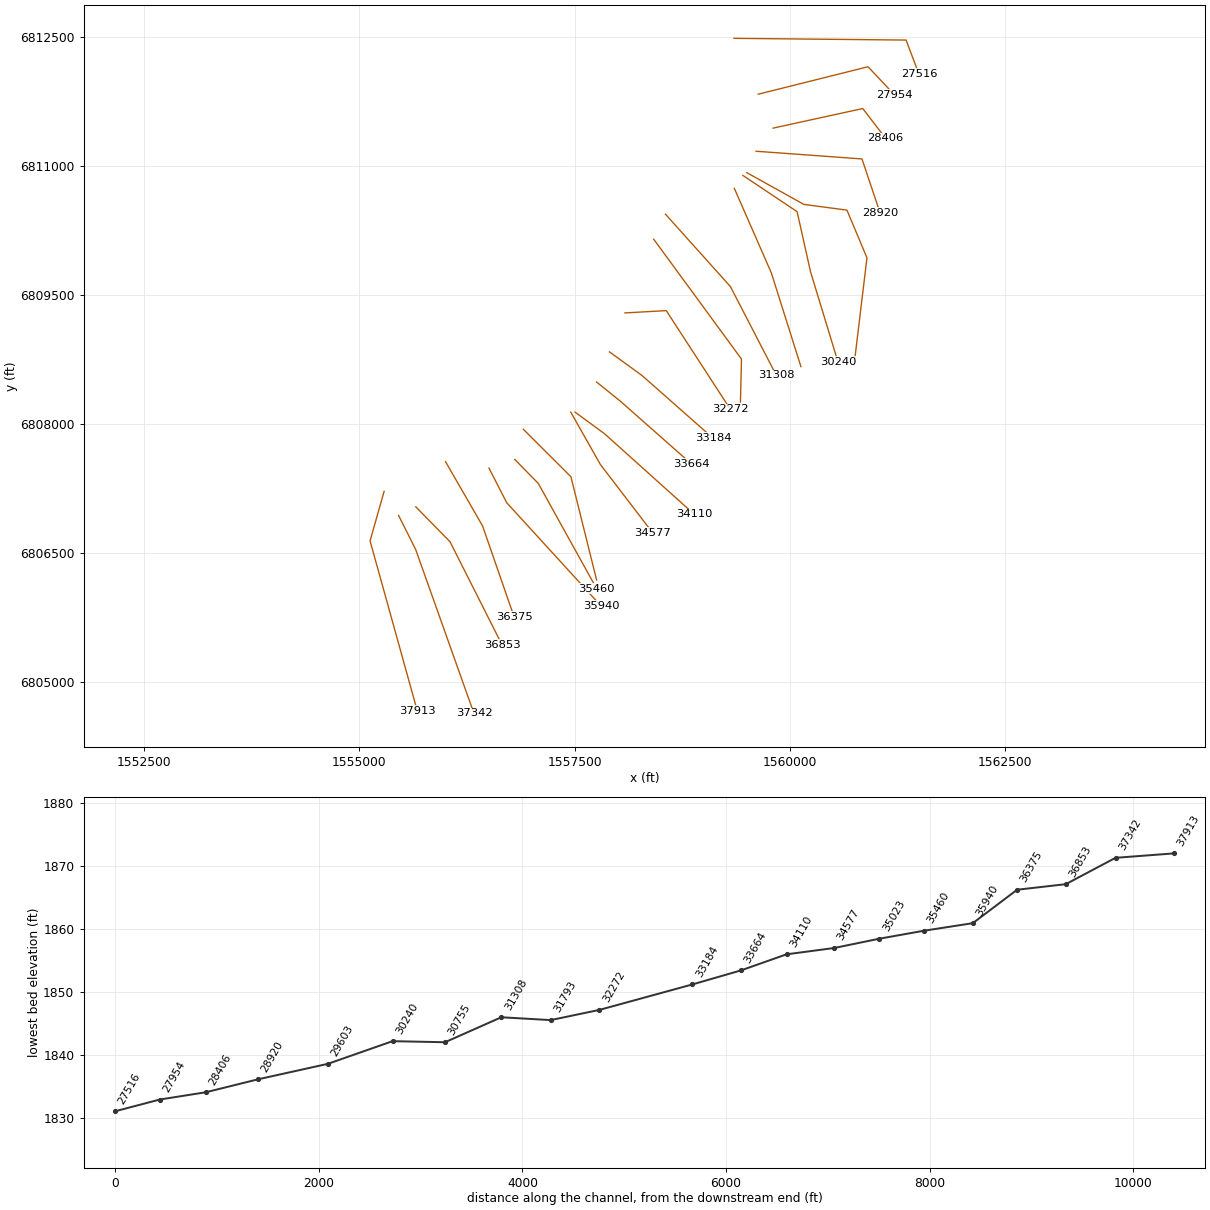
HEC-RAS study Elm 01 17.prj: Elm 01 17 Base Level Engineering

--- Elm 01 17.g01 (geometry) --- (continued)

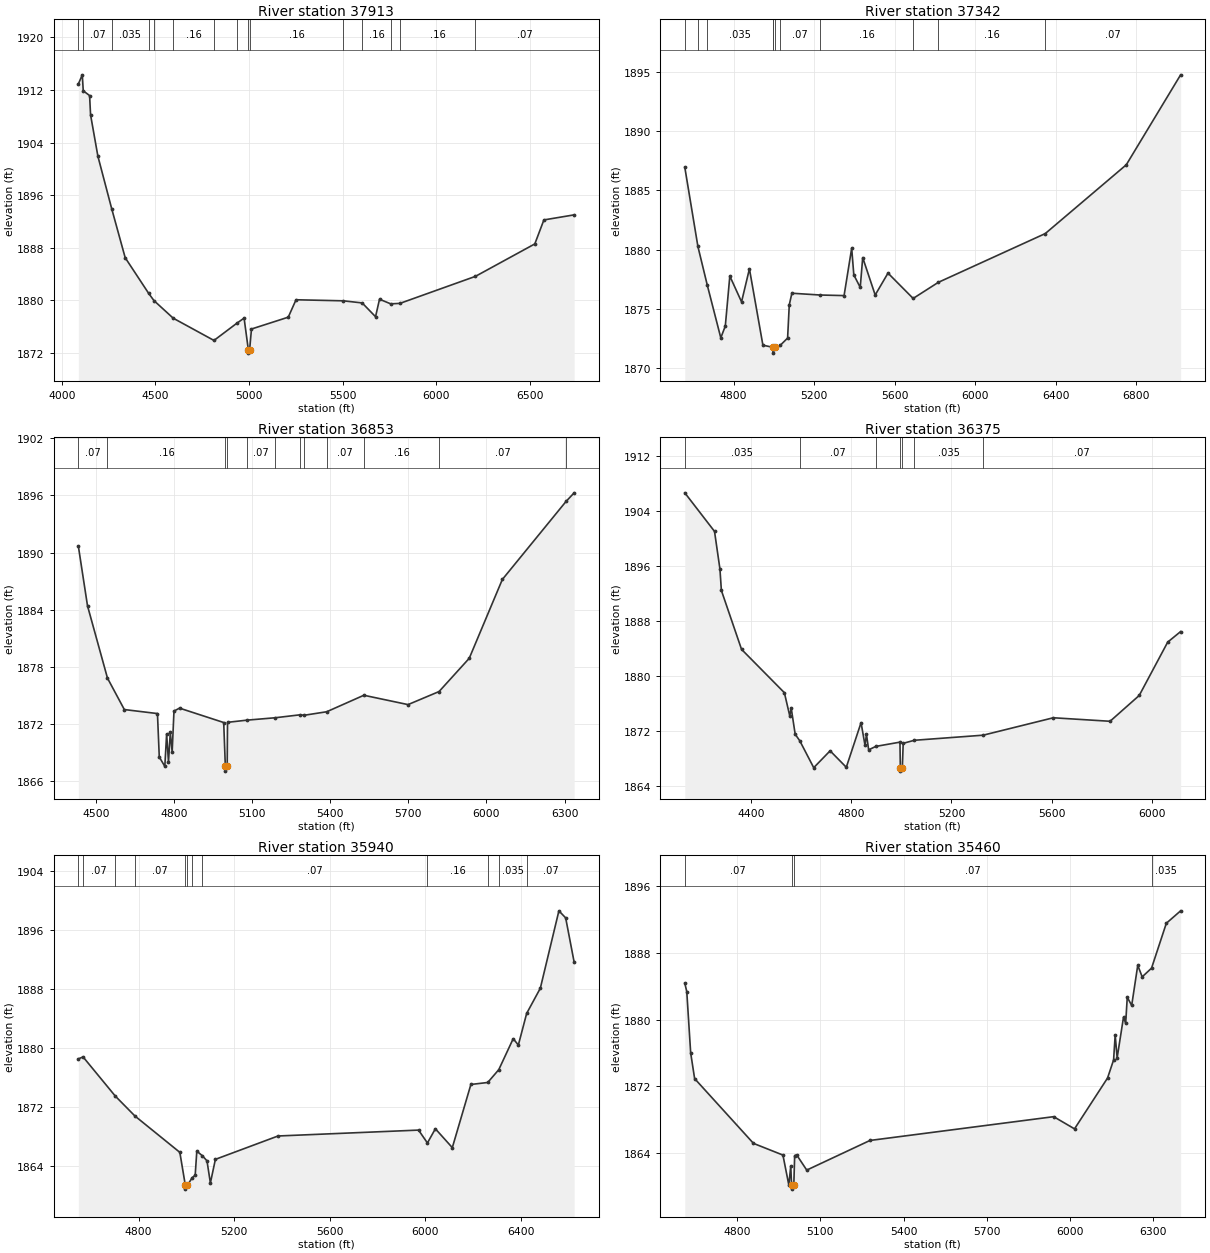
Type RM Length L Ch R = 1,37913,571,571,571
BEGIN DESCRIPTION:
Elm 01 14 22.0
END DESCRIPTION:
XS GIS Cut Line= 3
      1555287.16      6807218.32      1555123.71      6806642.51
      1555672.84      6804665.41
#Sta/Elev= 30
  4087.8 1912.90  4108.9 1914.31  4114.1 1911.88  4148.0 1911.15  4153.2 1908.22
  4192.3 1901.93  4266.3 1893.92  4338.3 1886.48  4464.1 1881.04  4492.2 1879.95
  4594.8 1877.28  4812.9 1873.89  4934.7 1876.50  4973.9 1877.29  4996.7 1872.46
  4997.2 1871.96  5003.4 1872.46  5013.4 1875.63  5210.0 1877.43  5251.5 1880.08
  5504.3 1879.92  5605.1 1879.60  5676.6 1877.50  5697.8 1880.16  5757.7 1879.46
  5806.9 1879.53  6210.4 1883.64  6528.0 1888.58  6576.5 1892.23  6738.3 1893.00
#Mann=15,-1,0
  4087.8   0.035       0  4114.1    0.07       0  4266.3   0.035       0
  4464.1    0.07       0  4492.2   0.035       0  4594.8    0.16       0
  4812.9    0.07       0  4934.7    0.16       0  4996.7    0.07       0
  5003.4    0.16       0  5504.3    0.07       0  5605.1    0.16       0
  5757.7    0.07       0  5806.9    0.16       0  6210.4    0.07       0
Bank Sta=4996.7,5003.4
Exp/Cntr=0.3,0.1

Type RM Length L Ch R = 1,37342,489,489,489
BEGIN DESCRIPTION:
Elm 01 14 21.0
END DESCRIPTION:
XS GIS Cut Line= 3
      1555455.02      6806937.96      1555653.35      6806542.39
      1556330.21      6804638.00
#Sta/Elev= 30
  4557.5 1886.96  4622.6 1880.27  4669.1 1877.01  4736.4 1872.55  4758.8 1873.55
  4781.2 1877.77  4839.5 1875.59  4878.6 1878.38  4945.6 1871.93  4993.3 1871.76
  4996.5 1871.76  4997.0 1871.26  5003.6 1871.76  5031.1 1871.91  5068.3 1872.53
  5076.6 1875.34  5089.6 1876.32  5229.0 1876.17  5348.9 1876.12  5386.7 1880.12
  5397.3 1877.87  5429.2 1876.81  5441.5 1879.33  5503.5 1876.17  5567.1 1878.02
  5692.1 1875.88  5817.2 1877.24  6348.6 1881.36  6751.1 1887.17  7021.1 1894.77
#Mann=11,-1,0
  4557.5   0.035       0  4622.6    0.07       0  4669.1   0.035       0
  4993.3    0.16       0  4996.5    0.07       0  5003.6    0.16       0
  5031.1    0.07       0  5229.0    0.16       0  5692.1    0.07       0
  5817.2    0.16       0  6348.6    0.07       0
Bank Sta=4996.5,5003.6
Exp/Cntr=0.3,0.1

Type RM Length L Ch R = 1,36853,478,478,478
BEGIN DESCRIPTION:
Elm 01 14 20.0
END DESCRIPTION:
XS GIS Cut Line= 3
      1555655.03      6807037.97      1556052.81      6806631.82
      1556655.00      6805438.00
#Sta/Elev= 30
  4431.5 1890.70  4466.8 1884.42  4543.5 1876.84  4608.3 1873.54  4735.6 1873.12
  4742.6 1868.56  4763.9 1867.58  4770.9 1871.00  4778.0 1868.05  4785.0 1871.15
  4792.1 1869.09  4799.1 1873.38  4820.4 1873.69  4990.2 1872.18  4996.5 1867.58
  4997.0 1867.08  5003.6 1867.58  5004.9 1872.20  5080.1 1872.43  5188.3 1872.68
  5283.9 1872.99  5299.3 1872.94  5386.1 1873.31  5528.8 1875.04  5698.7 1874.06
  5817.9 1875.43  5933.9 1878.92  6061.1 1887.19  6306.0 1895.38  6337.1 1896.28
#Mann=12,-1,0
  4431.5    0.07       0  4543.5    0.16       0  4996.5    0.07       0
  5003.6    0.16       0  5080.1    0.07       0  5188.3   0.035       0
  5283.9    0.07       0  5299.3   0.035       0  5386.1    0.07       0
  5528.8    0.16       0  5817.9    0.07       0  6306.0   0.035       0
Bank Sta=4996.5,5003.6
Exp/Cntr=0.3,0.1

Type RM Length L Ch R = 1,36375,435,435,435
BEGIN DESCRIPTION:
Elm 01 14 19.0
END DESCRIPTION:
XS GIS Cut Line= 3
      1555999.66      6807563.85      1556430.90      6806815.04
      1556796.01      6805761.94
#Sta/Elev= 30
  4135.9 1906.62  4254.5 1901.02  4276.1 1895.56  4281.9 1892.44  4362.3 1883.89
  4533.3 1877.59  4554.8 1874.22  4560.6 1875.35  4576.4 1871.56  4594.7 1870.61
  4650.4 1866.70  4715.8 1869.15  4780.4 1866.76  4839.3 1873.24  4855.1 1869.95
  4860.9 1871.54  4869.6 1869.29  4898.1 1869.79  4994.5 1870.41  4996.1 1866.70
  4996.6 1866.20  5004.0 1866.70  5007.5 1870.24  5051.9 1870.68  5326.5 1871.42
  5606.6 1873.95  5833.0 1873.44  5949.4 1877.19  6063.1 1884.94  6114.6 1886.47
#Mann=7,-1,0
  4135.9   0.035       0  4594.7    0.07       0  4898.1    0.16       0
  4996.1    0.07       0  5004.0    0.16       0  5051.9   0.035       0
  5326.5    0.07       0
Bank Sta=4996.1,5004
Exp/Cntr=0.3,0.1

Type RM Length L Ch R = 1,35940,480,480,480
BEGIN DESCRIPTION:
Elm 01 14 18.0
END DESCRIPTION:
XS GIS Cut Line= 3
      1556505.00      6807488.00      1556710.86      6807085.93
      1557805.00      6805888.00
#Sta/Elev= 30
  4548.3 1878.57  4568.1 1878.84  4702.5 1873.54  4785.1 1870.82  4972.9 1865.89
  4996.0 1861.40  4996.5 1860.90  5004.0 1861.40  5025.1 1862.47  5037.1 1862.78
  5043.9 1866.05  5067.1 1865.43  5086.5 1864.74  5100.7 1861.73  5121.6 1864.94
  5383.7 1868.11  5971.5 1868.91  6008.6 1867.16  6041.8 1869.09  6112.7 1866.53
  6190.4 1875.10  6260.9 1875.37  6307.1 1877.11  6367.4 1881.31  6389.0 1880.45
  6423.7 1884.74  6480.9 1888.16  6558.6 1898.66  6586.9 1897.70  6622.4 1891.69
#Mann=12,-1,0
  4548.3   0.035       0  4568.1    0.07       0  4702.5   0.035       0
  4785.1    0.07       0  4996.0    0.07       0  5004.0    0.07       0
  5025.1    0.16       0  5067.1    0.07       0  6008.6    0.16       0
  6260.9    0.07       0  6307.1   0.035       0  6423.7    0.07       0
Bank Sta=4996,5004
Exp/Cntr=0.3,0.1

Type RM Length L Ch R = 1,35460,437,437,437
BEGIN DESCRIPTION:
Elm 01 14 17.0
END DESCRIPTION:
XS GIS Cut Line= 3
      1556804.98      6807588.02      1557077.24      6807310.59
      1557755.01      6806087.99
#Sta/Elev= 30
  4611.3 1884.36  4618.4 1883.37  4632.5 1876.01  4646.7 1872.94  4858.8 1865.18
  4964.9 1863.78  4986.1 1860.20  4993.1 1862.46  4996.0 1860.20  4996.5 1859.70
  5004.1 1860.20  5007.2 1863.72  5014.4 1863.80  5050.7 1861.98  5278.5 1865.53
  5940.5 1868.38  6015.6 1866.92  6134.6 1873.01  6156.4 1875.18  6162.1 1878.17
  6169.2 1875.43  6192.1 1880.30  6199.9 1879.57  6205.6 1882.68  6221.6 1881.71
  6243.4 1886.51  6259.4 1885.13  6293.1 1886.17  6346.4 1891.55  6397.9 1893.04
#Mann=4,-1,0
  4611.3    0.07       0  4996.0    0.07       0  5004.1    0.07       0
  6293.1   0.035       0
Bank Sta=4996,5004.1
Exp/Cntr=0.3,0.1

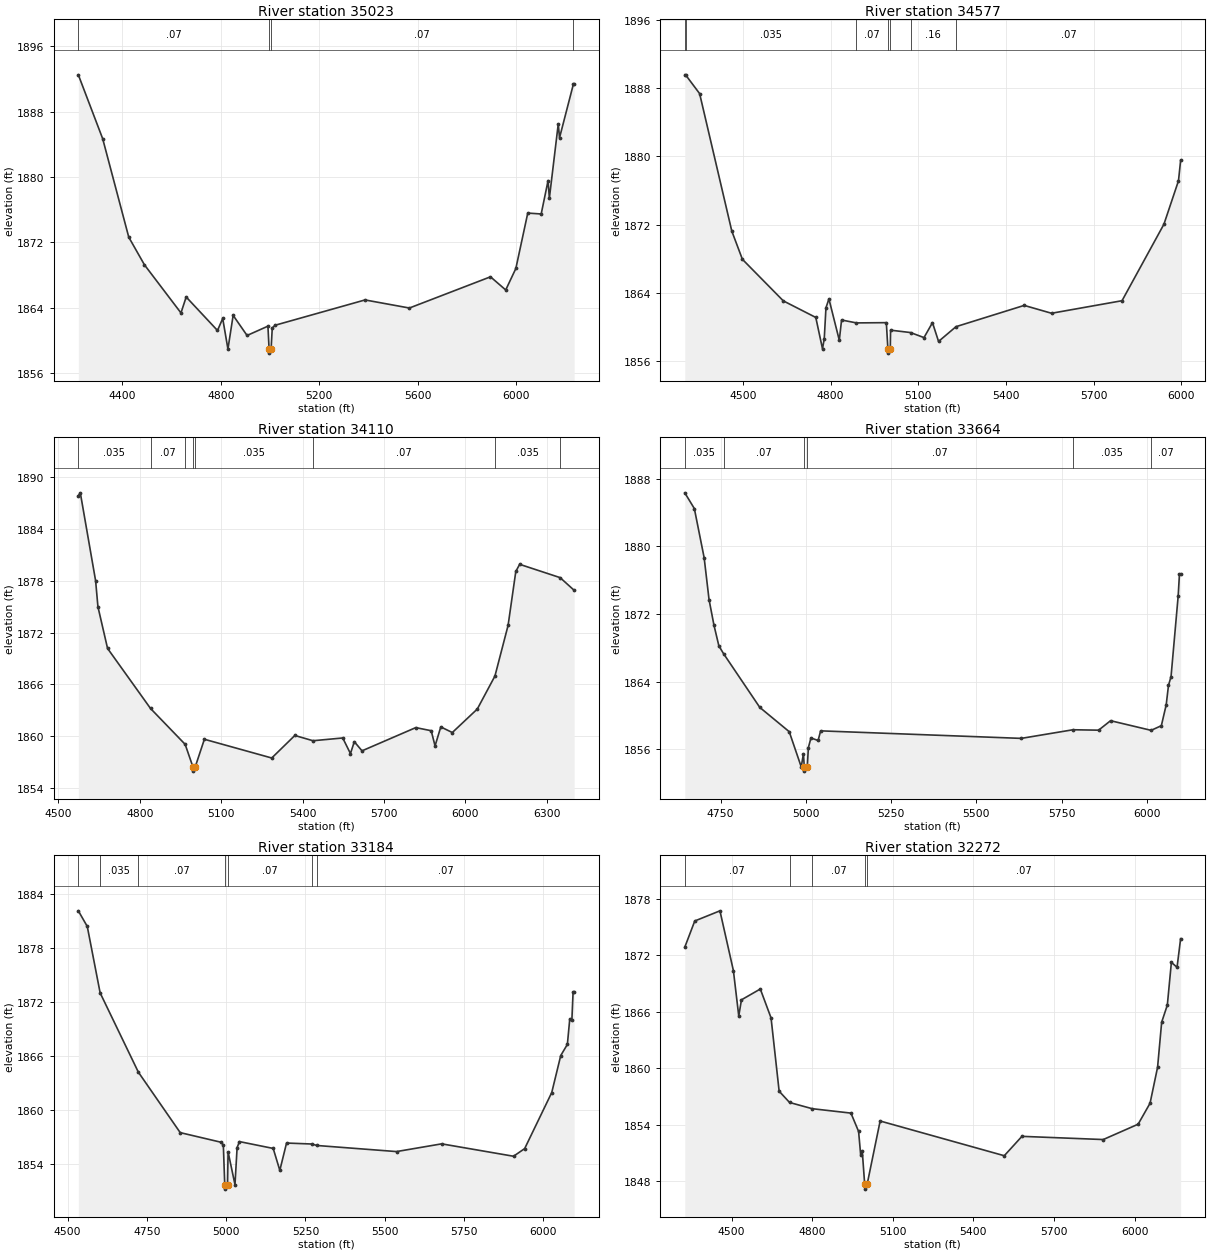
Type RM Length L Ch R = 1,35023,446,446,446
BEGIN DESCRIPTION:
Elm 01 14 16.0
END DESCRIPTION:
XS GIS Cut Line= 3
      1556905.01      6807937.99      1557456.88      6807387.48
      1557755.01      6806187.97
#Sta/Elev= 30
  4220.5 1892.50  4319.5 1884.68  4425.5 1872.63  4489.2 1869.25  4637.7 1863.36
  4658.9 1865.31  4786.2 1861.21  4807.4 1862.68  4828.6 1858.94  4849.8 1863.06
  4906.4 1860.60  4991.2 1861.74  4995.9 1858.94  4996.4 1858.44  5004.1 1858.94
  5008.8 1861.51  5020.1 1861.85  5386.0 1864.95  5566.2 1863.96  5895.9 1867.78
  5957.8 1866.17  5999.0 1868.80  6047.4 1875.58  6102.0 1875.47  6130.0 1879.56
  6135.2 1877.40  6171.4 1886.50  6176.5 1884.79  6232.8 1891.35  6236.0 1891.37
#Mann=4,-1,0
  4220.5    0.07       0  4995.9    0.07       0  5004.1    0.07       0
  6232.8   0.035       0
Bank Sta=4995.9,5004.1
Exp/Cntr=0.3,0.1

Type RM Length L Ch R = 1,34577,467,467,467
BEGIN DESCRIPTION:
Elm 01 14 15.0
END DESCRIPTION:
XS GIS Cut Line= 3
      1557455.02      6808137.97      1557798.97      6807529.80
      1558405.00      6806738.00
#Sta/Elev= 30
  4301.3 1889.56  4305.0 1889.51  4352.0 1887.36  4462.1 1871.25  4498.3 1867.95
  4638.3 1863.08  4749.3 1861.14  4772.3 1857.46  4778.3 1858.67  4784.1 1862.27
  4794.2 1863.31  4829.7 1858.47  4837.5 1860.84  4888.4 1860.50  4990.6 1860.53
  4995.9 1857.46  4996.4 1856.96  5004.1 1857.46  5005.1 1859.65  5073.3 1859.37
  5119.4 1858.78  5148.4 1860.53  5169.2 1858.33  5228.9 1860.06  5462.1 1862.55
  5555.6 1861.63  5796.7 1863.10  5940.0 1872.06  5989.8 1877.15  5997.1 1879.53
#Mann=7,-1,0
  4301.3    0.07       0  4305.0   0.035       0  4888.4    0.07       0
  4995.9    0.07       0  5004.1    0.07       0  5073.3    0.16       0
  5228.9    0.07       0
Bank Sta=4995.9,5004.1
Exp/Cntr=0.3,0.1

Type RM Length L Ch R = 1,34110,446,446,446
BEGIN DESCRIPTION:
Elm 01 14 14.0
END DESCRIPTION:
XS GIS Cut Line= 3
      1557504.99      6808138.01      1557848.82      6807885.81
      1558890.52      6806949.88
#Sta/Elev= 30
  4573.6 1887.85  4580.9 1888.19  4637.3 1878.00  4645.8 1875.00  4681.3 1870.17
  4839.5 1863.22  4967.2 1859.06  4995.7 1856.46  4996.2 1855.96  5004.4 1856.46
  5038.0 1859.65  5286.2 1857.48  5371.3 1860.09  5438.1 1859.48  5547.8 1859.80
  5576.2 1857.99  5590.4 1859.37  5618.8 1858.31  5816.9 1861.00  5873.7 1860.64
  5887.9 1858.88  5909.0 1861.08  5951.5 1860.43  6043.5 1863.15  6108.5 1866.97
  6157.0 1872.84  6185.4 1879.08  6199.6 1879.91  6348.6 1878.37  6400.4 1876.90
#Mann=8,-1,0
  4573.6   0.035       0  4839.5    0.07       0  4967.2   0.035       0
  4995.7   0.035       0  5004.4   0.035       0  5438.1    0.07       0
  6108.5   0.035       0  6348.6    0.07       0
Bank Sta=4995.7,5004.4
Exp/Cntr=0.3,0.1

Type RM Length L Ch R = 1,33664,480,480,480
BEGIN DESCRIPTION:
Elm 01 14 13.0
END DESCRIPTION:
XS GIS Cut Line= 3
      1557755.04      6808487.97      1558031.05      6808265.19
      1558855.03      6807537.97
#Sta/Elev= 30
  4645.3 1886.31  4673.3 1884.45  4702.0 1878.65  4716.4 1873.69  4730.8 1870.67
  4745.2 1868.22  4758.8 1867.31  4865.2 1860.95  4951.5 1858.08  4986.7 1853.92
  4993.1 1855.48  4995.6 1853.92  4996.1 1853.42  5004.4 1853.92  5007.6 1856.20
  5015.2 1857.34  5036.1 1857.04  5043.6 1858.18  5631.8 1857.29  5783.5 1858.31
  5858.5 1858.26  5893.6 1859.38  6012.5 1858.24  6042.5 1858.79  6056.7 1861.25
  6063.4 1863.55  6070.9 1864.59  6091.8 1874.11  6095.6 1876.72  6099.0 1876.72
#Mann=6,-1,0
  4645.3   0.035       0  4758.8    0.07       0  4995.6    0.07       0
  5004.4    0.07       0  5783.5   0.035       0  6012.5    0.07       0
Bank Sta=4995.6,5004.4
Exp/Cntr=0.3,0.1

Type RM Length L Ch R = 1,33184,912,912,912
BEGIN DESCRIPTION:
Elm 01 14 12.0
END DESCRIPTION:
XS GIS Cut Line= 3
      1557904.97      6808838.02      1558282.14      6808564.16
      1559105.03      6807837.97
#Sta/Elev= 30
  4533.9 1882.16  4562.1 1880.42  4602.7 1873.02  4723.2 1864.20  4855.2 1857.47
  4985.0 1856.39  4991.2 1856.06  4995.6 1851.68  4996.1 1851.18  5004.4 1851.68
  5006.1 1855.34  5027.9 1851.68  5034.6 1855.81  5042.1 1856.47  5148.4 1855.71
  5169.3 1853.27  5190.5 1856.31  5271.5 1856.20  5285.6 1856.04  5537.3 1855.36
  5679.6 1856.22  5906.3 1854.84  5941.4 1855.69  6026.8 1861.93  6055.2 1866.05
  6076.1 1867.29  6083.7 1870.15  6090.3 1870.00  6094.1 1873.10  6097.5 1873.10
#Mann=7,-1,0
  4533.9    0.07       0  4602.7   0.035       0  4723.2    0.07       0
  4995.6    0.07       0  5004.4    0.07       0  5271.5   0.035       0
  5285.6    0.07       0
Bank Sta=4995.6,5004.4
Exp/Cntr=0.3,0.1

Type RM Length L Ch R = 1,32272,479,479,479
BEGIN DESCRIPTION:
Elm 01 14 11.0
END DESCRIPTION:
XS GIS Cut Line= 3
      1558084.39      6809290.86      1558564.19      6809317.63
      1559307.67      6808172.58
#Sta/Elev= 30
  4325.8 1872.87  4362.9 1875.65  4456.6 1876.73  4506.7 1870.38  4526.7 1865.55
  4536.7 1867.27  4606.9 1868.42  4646.9 1865.35  4677.0 1857.56  4715.8 1856.36
  4799.9 1855.70  4944.3 1855.23  4972.8 1853.28  4980.5 1850.80  4986.5 1851.17
  4995.5 1847.65  4996.0 1847.15  5004.5 1847.65  5053.0 1854.39  5515.1 1850.70
  5580.9 1852.76  5883.5 1852.42  6013.4 1854.05  6057.8 1856.28  6085.8 1860.10
  6101.0 1864.89  6122.1 1866.71  6137.2 1871.25  6158.3 1870.73  6171.6 1873.77
#Mann=5,-1,0
  4325.8    0.07       0  4715.8   0.035       0  4799.9    0.07       0
  4995.5    0.07       0  5004.5    0.07       0
Bank Sta=4995.5,5004.5
Exp/Cntr=0.3,0.1

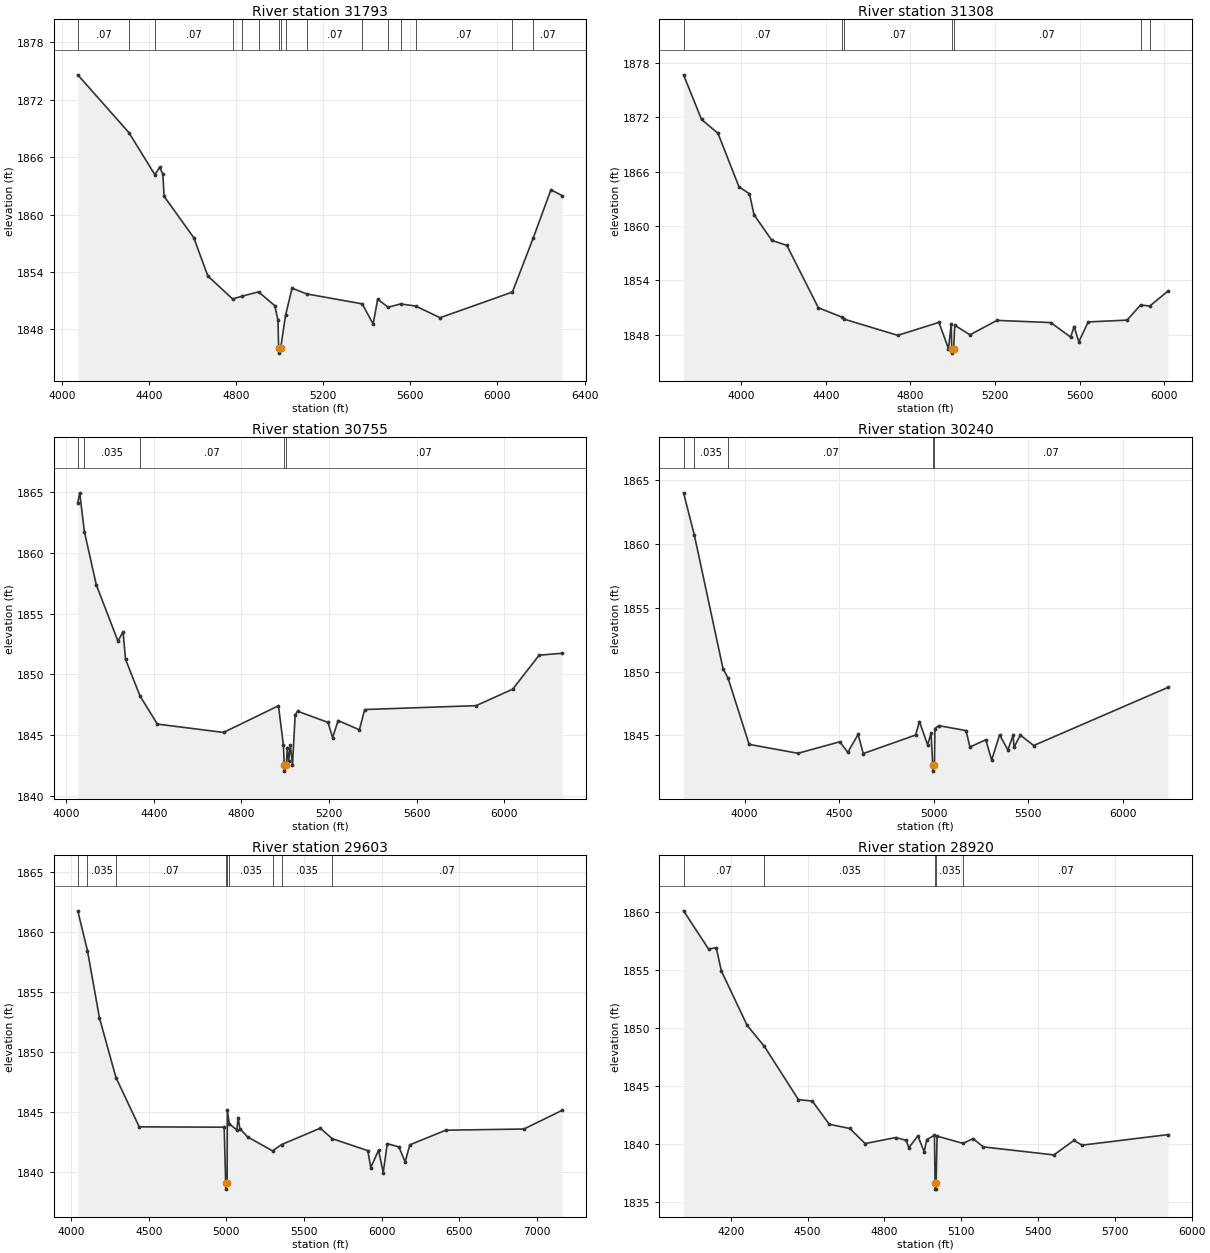
Type RM Length L Ch R = 1,31793,485,485,485
BEGIN DESCRIPTION:
Elm 01 14 10.0
END DESCRIPTION:
XS GIS Cut Line= 3
      1558418.57      6810146.91      1559437.96      6808754.96
      1559426.10      6808256.01
#Sta/Elev= 30
  4073.1 1874.61  4308.0 1868.57  4427.1 1864.18  4448.8 1864.94  4463.5 1864.27
  4469.7 1861.91  4605.6 1857.60  4670.4 1853.59  4784.1 1851.19  4826.0 1851.47
  4903.1 1851.93  4977.7 1850.49  4992.3 1849.00  4995.5 1846.03  4996.0 1845.53
  5004.5 1846.03  5027.4 1849.52  5057.2 1852.32  5123.6 1851.72  5379.2 1850.68
  5429.3 1848.57  5450.1 1851.16  5498.2 1850.33  5555.5 1850.67  5624.7 1850.45
  5736.5 1849.23  6068.7 1851.91  6164.2 1857.55  6245.5 1862.59  6297.5 1861.99
#Mann=16,-1,0
  4073.1    0.07       0  4308.0   0.035       0  4427.1    0.07       0
  4784.1   0.035       0  4826.0    0.07       0  4903.1   0.035       0
  4995.5   0.035       0  5004.5   0.035       0  5027.4   0.035       0
  5123.6    0.07       0  5379.2   0.035       0  5498.2    0.07       0
  5555.5   0.035       0  5624.7    0.07       0  6068.7   0.035       0
  6164.2    0.07       0
Bank Sta=4995.5,5004.5
Exp/Cntr=0.3,0.1

Type RM Length L Ch R = 1,31308,553,553,553
BEGIN DESCRIPTION:
Elm 01 14 9.0
END DESCRIPTION:
XS GIS Cut Line= 3
      1558554.98      6810438.02      1559309.21      6809597.17
      1559842.57      6808565.99
#Sta/Elev= 30
  3727.5 1876.66  3812.4 1871.74  3890.1 1870.22  3989.5 1864.31  4038.9 1863.55
  4060.6 1861.24  4145.0 1858.41  4216.0 1857.85  4364.8 1850.98  4476.1 1849.95
  4486.3 1849.73  4740.1 1847.94  4934.9 1849.37  4980.0 1846.48  4993.1 1849.22
  4995.5 1846.48  4996.0 1845.98  5004.5 1846.48  5009.6 1849.05  5081.7 1848.00
  5208.9 1849.59  5463.3 1849.35  5557.5 1847.75  5574.0 1848.91  5596.2 1847.23
  5640.5 1849.42  5824.3 1849.62  5888.1 1851.28  5932.2 1851.18  6018.0 1852.83
#Mann=7,-1,0
  3727.5    0.07       0  4476.1   0.035       0  4486.3    0.07       0
  4995.5    0.07       0  5004.5    0.07       0  5888.1   0.035       0
  5932.2    0.07       0
Bank Sta=4995.5,5004.5
Exp/Cntr=0.3,0.1

Type RM Length L Ch R = 1,30755,515,515,515
BEGIN DESCRIPTION:
Elm 01 14 8.0
END DESCRIPTION:
XS GIS Cut Line= 3
      1559355.01      6810737.99      1559785.08      6809755.35
      1560128.18      6808667.50
#Sta/Elev= 30
  4052.3 1864.15  4061.2 1864.97  4082.5 1861.78  4136.9 1857.39  4235.9 1852.74
  4259.3 1853.52  4270.6 1851.24  4336.7 1848.22  4415.9 1845.90  4718.4 1845.21
  4969.2 1847.41  4992.0 1844.15  4995.5 1842.52  4996.0 1842.02  5004.6 1842.52
  5010.0 1843.96  5015.4 1842.82  5023.8 1844.15  5033.3 1842.52  5045.6 1846.67
  5056.5 1846.96  5195.6 1846.04  5216.5 1844.78  5241.9 1846.19  5338.9 1845.43
  5363.3 1847.10  5872.3 1847.42  6039.3 1848.78  6160.2 1851.58  6265.6 1851.74
#Mann=5,-1,0
  4052.3    0.07       0  4082.5   0.035       0  4336.7    0.07       0
  4995.5    0.07       0  5004.6    0.07       0
Bank Sta=4995.5,5004.6
Exp/Cntr=0.3,0.1

Type RM Length L Ch R = 1,30240,637,637,637
BEGIN DESCRIPTION:
Elm 01 14 7.0
END DESCRIPTION:
XS GIS Cut Line= 4
      1559455.04      6810887.97      1560083.95      6810467.39
      1560240.18      6809768.59      1560557.60      6808725.45
#Sta/Elev= 30
  3677.2 1864.02  3734.5 1860.68  3885.9 1850.23  3912.2 1849.50  4024.0 1844.29
  4282.2 1843.59  4503.6 1844.49  4545.9 1843.67  4600.6 1845.07  4627.8 1843.57
  4904.5 1845.02  4925.0 1846.08  4968.4 1844.25  4986.5 1845.17  4995.4 1842.69
  4995.9 1842.19  5004.6 1842.69  5006.7 1845.52  5027.5 1845.76  5171.4 1845.37
  5192.3 1844.08  5275.9 1844.65  5307.2 1843.06  5349.1 1845.04  5392.9 1843.85
  5420.5 1845.00  5425.7 1844.06  5458.6 1845.02  5529.5 1844.20  6240.2 1848.76
#Mann=5,-1,0
  3677.2    0.07       0  3734.5   0.035       0  3912.2    0.07       0
  4995.4    0.07       0  5004.6    0.07       0
Bank Sta=4995.4,5004.6
Exp/Cntr=0.3,0.1

Type RM Length L Ch R = 1,29603,683,683,683
BEGIN DESCRIPTION:
Elm 01 14 6.5
END DESCRIPTION:
XS GIS Cut Line= 5
      1559498.69      6810921.35      1560163.06      6810551.77
      1560662.90      6810485.19      1560895.52      6809931.19
      1560745.31      6808682.56
#Sta/Elev= 30
  4041.8 1861.78  4104.5 1858.45  4181.5 1852.87  4288.0 1847.89  4438.1 1843.78
  4985.6 1843.75  4995.4 1839.09  4995.9 1838.59  5004.7 1839.09  5005.8 1845.19
  5018.4 1844.04  5066.3 1843.52  5076.4 1844.55  5086.5 1843.63  5136.9 1842.94
  5297.2 1841.78  5355.4 1842.30  5605.1 1843.67  5683.0 1842.79  5911.3 1841.80
  5930.5 1840.39  5980.9 1841.83  6011.1 1839.97  6036.7 1842.38  6111.8 1842.11
  6152.1 1840.86  6182.3 1842.28  6414.0 1843.50  6917.6 1843.60  7164.8 1845.16
#Mann=9,-1,0
  4041.8    0.07       0  4104.5   0.035       0  4288.0    0.07       0
  4995.4    0.07       0  5004.7    0.07       0  5018.4   0.035       0
  5297.2    0.07       0  5355.4   0.035       0  5683.0    0.07       0
Bank Sta=4995.4,5004.7
Exp/Cntr=0.3,0.1

Type RM Length L Ch R = 1,28920,514,514,514
BEGIN DESCRIPTION:
Elm 01 14 6.0
END DESCRIPTION:
XS GIS Cut Line= 3
      1559607.74      6811169.50      1560837.57      6811079.94
      1561047.01      6810455.19
#Sta/Elev= 30
  4015.7 1860.14  4113.2 1856.85  4143.3 1856.96  4163.3 1854.96  4263.6 1850.28
  4331.1 1848.46  4464.1 1843.87  4518.8 1843.74  4584.5 1841.74  4664.7 1841.38
  4724.8 1840.08  4845.2 1840.60  4885.3 1840.35  4895.3 1839.72  4930.8 1840.74
  4955.4 1839.37  4965.5 1840.42  4995.5 1840.79  4998.0 1836.65  4998.3 1836.15
  5001.8 1836.15  5002.0 1836.65  5005.6 1840.72  5107.6 1840.09  5145.9 1840.51
  5186.1 1839.79  5461.8 1839.10  5540.2 1840.35  5571.8 1839.94  5907.7 1840.85
#Mann=5,-1,0
  4015.7    0.07       0  4331.1   0.035       0  4998.0   0.035       0
  5002.0   0.035       0  5107.6    0.07       0
Bank Sta=4998,5002
Exp/Cntr=0.3,0.1

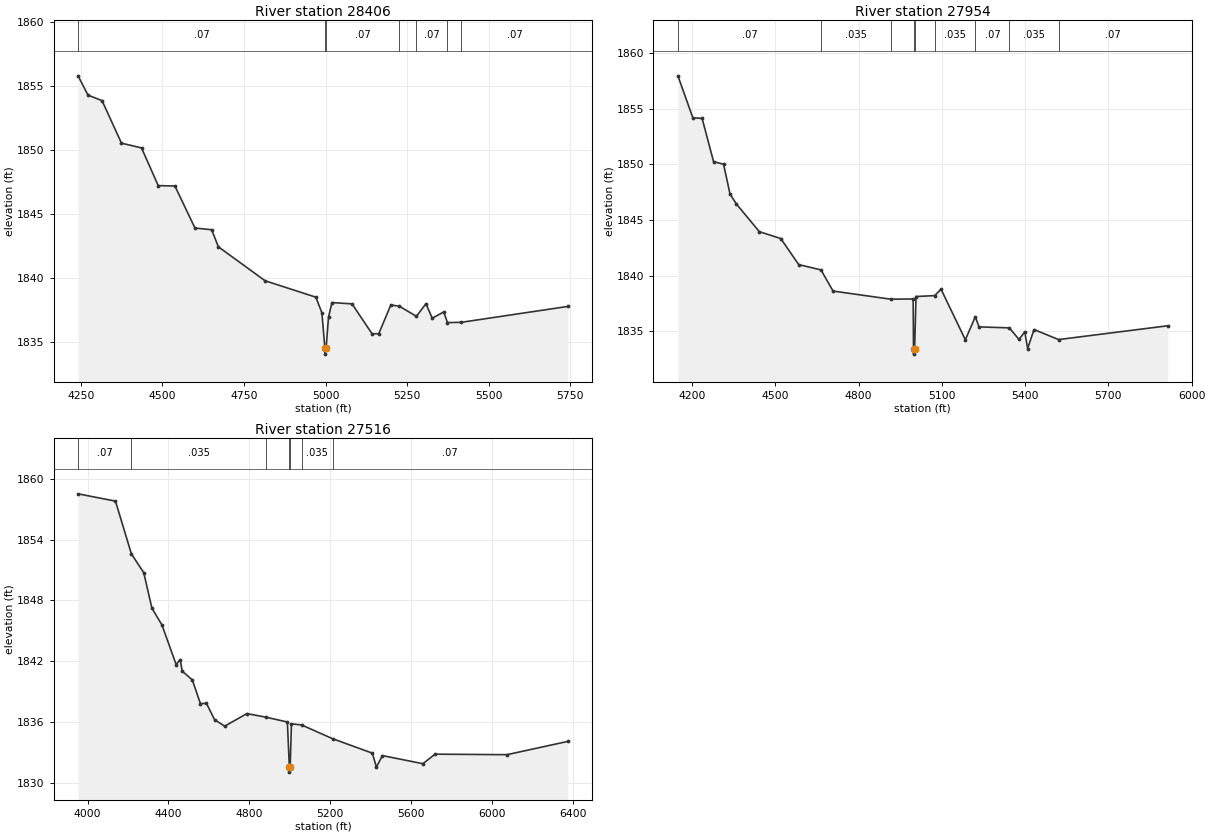
Type RM Length L Ch R = 1,28406,452,452,452
BEGIN DESCRIPTION:
Elm 01 14 5.0
END DESCRIPTION:
XS GIS Cut Line= 3
      1559805.01      6811438.00      1560846.40      6811665.75
      1561111.31      6811320.97
#Sta/Elev= 30
  4241.8 1855.79  4272.5 1854.28  4315.3 1853.86  4374.9 1850.54  4436.3 1850.17
  4487.5 1847.23  4538.6 1847.20  4600.1 1843.92  4651.2 1843.79  4671.7 1842.46
  4815.0 1839.81  4970.5 1838.53  4989.0 1837.31  4998.0 1834.59  4998.3 1834.09
  5002.0 1834.59  5009.2 1836.97  5019.8 1838.11  5081.2 1838.01  5142.6 1835.68
  5163.1 1835.68  5200.1 1837.92  5225.9 1837.83  5278.5 1837.04  5307.8 1838.02
  5327.0 1836.89  5362.3 1837.38  5373.6 1836.55  5415.8 1836.57  5742.6 1837.81
#Mann=7,-1,0
  4241.8    0.07       0  4998.0    0.07       0  5002.0    0.07       0
  5225.9   0.035       0  5278.5    0.07       0  5373.6   0.035       0
  5415.8    0.07       0
Bank Sta=4998,5002
Exp/Cntr=0.3,0.1

Type RM Length L Ch R = 1,27954,438,438,438
BEGIN DESCRIPTION:
Elm 01 14 4.0
END DESCRIPTION:
XS GIS Cut Line= 3
      1559632.88      6811832.46      1560907.89      6812151.33
      1561216.25      6811823.15
#Sta/Elev= 30
  4149.3 1857.96  4203.0 1854.19  4236.5 1854.13  4277.7 1850.25  4313.8 1850.01
  4337.0 1847.33  4360.2 1846.43  4442.6 1843.95  4519.9 1843.33  4584.4 1840.99
  4664.8 1840.51  4708.1 1838.61  4915.7 1837.88  4996.7 1837.90  4998.0 1833.44
  4998.3 1832.94  5002.0 1833.44  5007.0 1838.12  5074.3 1838.20  5097.1 1838.78
  5184.7 1834.23  5220.8 1836.31  5233.8 1835.39  5343.1 1835.30  5378.1 1834.26
  5398.8 1834.95  5409.1 1833.44  5432.0 1835.15  5520.6 1834.25  5913.9 1835.49
#Mann=9,-1,0
  4149.3    0.07       0  4664.8   0.035       0  4915.7    0.07       0
  4998.0    0.07       0  5002.0    0.07       0  5074.3   0.035       0
  5220.8    0.07       0  5343.1   0.035       0  5520.6    0.07       0
Bank Sta=4998,5002
Exp/Cntr=0.3,0.1

Type RM Length L Ch R = 1,27516,478,478,478
BEGIN DESCRIPTION:
Elm 01 14 3.0
END DESCRIPTION:
XS GIS Cut Line= 3
      1559349.91      6812481.33      1561350.05      6812461.21
      1561498.77      6812066.54
#Sta/Elev= 30
  3953.1 1858.51  4138.2 1857.79  4217.0 1852.59  4278.2 1850.73  4318.2 1847.25
  4368.2 1845.58  4438.2 1841.68  4458.2 1842.18  4468.2 1841.03  4518.2 1840.17
  4558.2 1837.83  4588.2 1837.86  4628.2 1836.25  4678.2 1835.61  4788.2 1836.85
  4881.1 1836.50  4988.2 1836.02  4998.0 1831.58  4998.3 1831.08  5002.0 1831.58
  5008.2 1835.84  5058.6 1835.73  5212.3 1834.37  5408.3 1832.95  5428.3 1831.58
  5458.3 1832.71  5658.3 1831.91  5718.3 1832.85  6074.3 1832.80  6375.1 1834.11
#Mann=7,-1,0
  3953.1    0.07       0  4217.0   0.035       0  4881.1    0.07       0
  4998.0    0.07       0  5002.0    0.07       0  5058.6   0.035       0
  5212.3    0.07       0
Bank Sta=4998,5002
Exp/Cntr=0.3,0.1