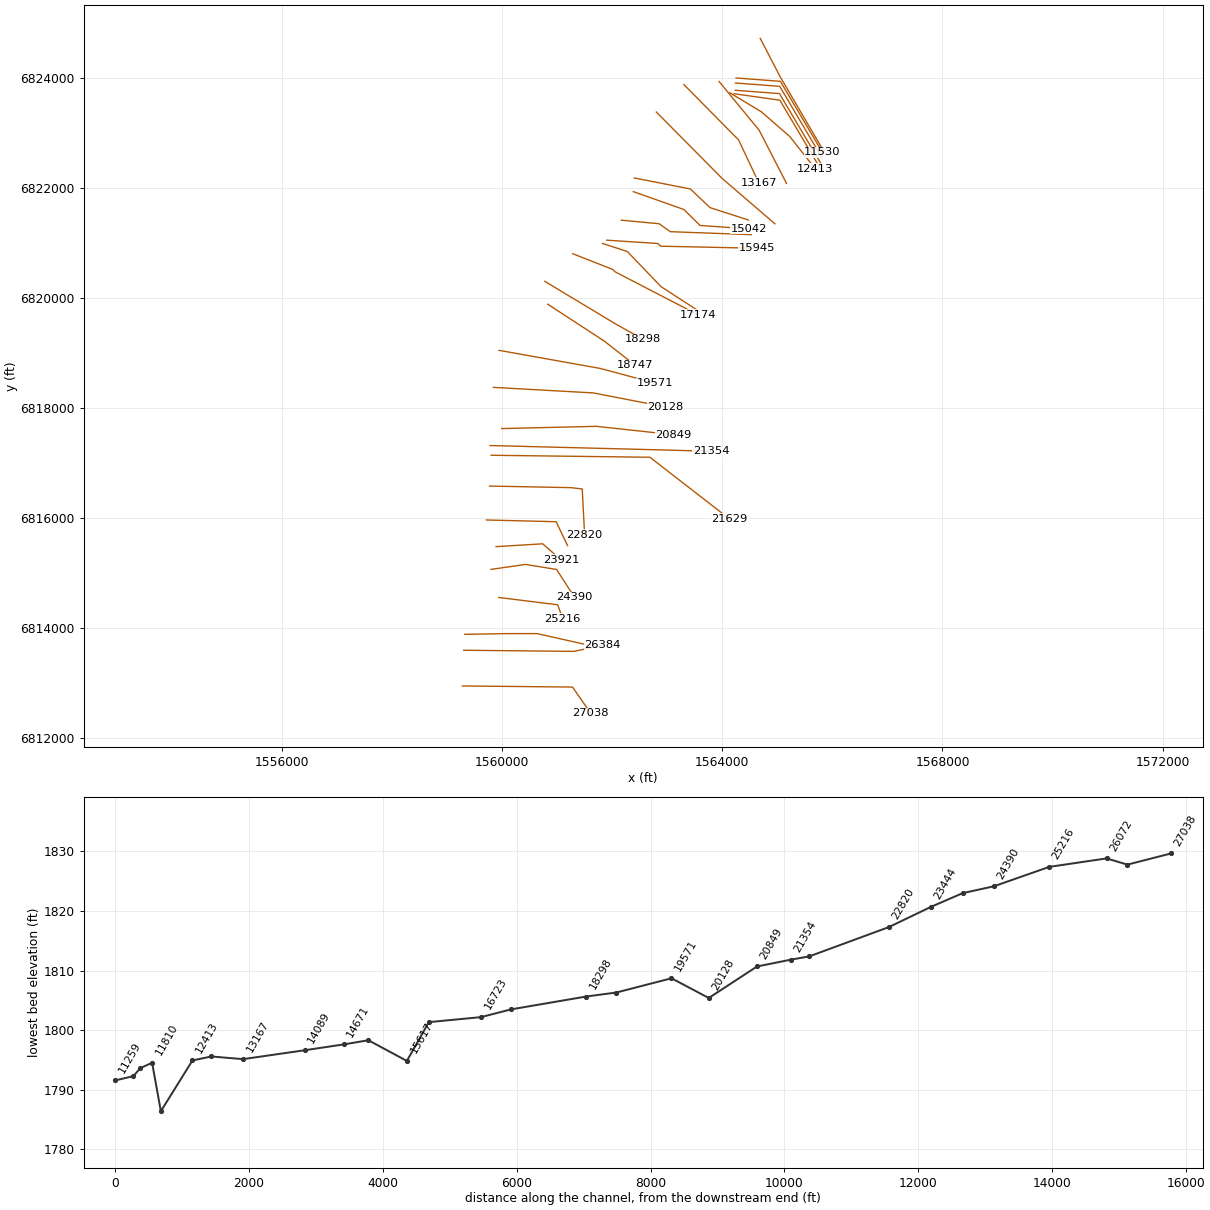
HEC-RAS study Elm 01 17.prj: Elm 01 17 Base Level Engineering

--- Elm 01 17.g01 (geometry) --- (continued)

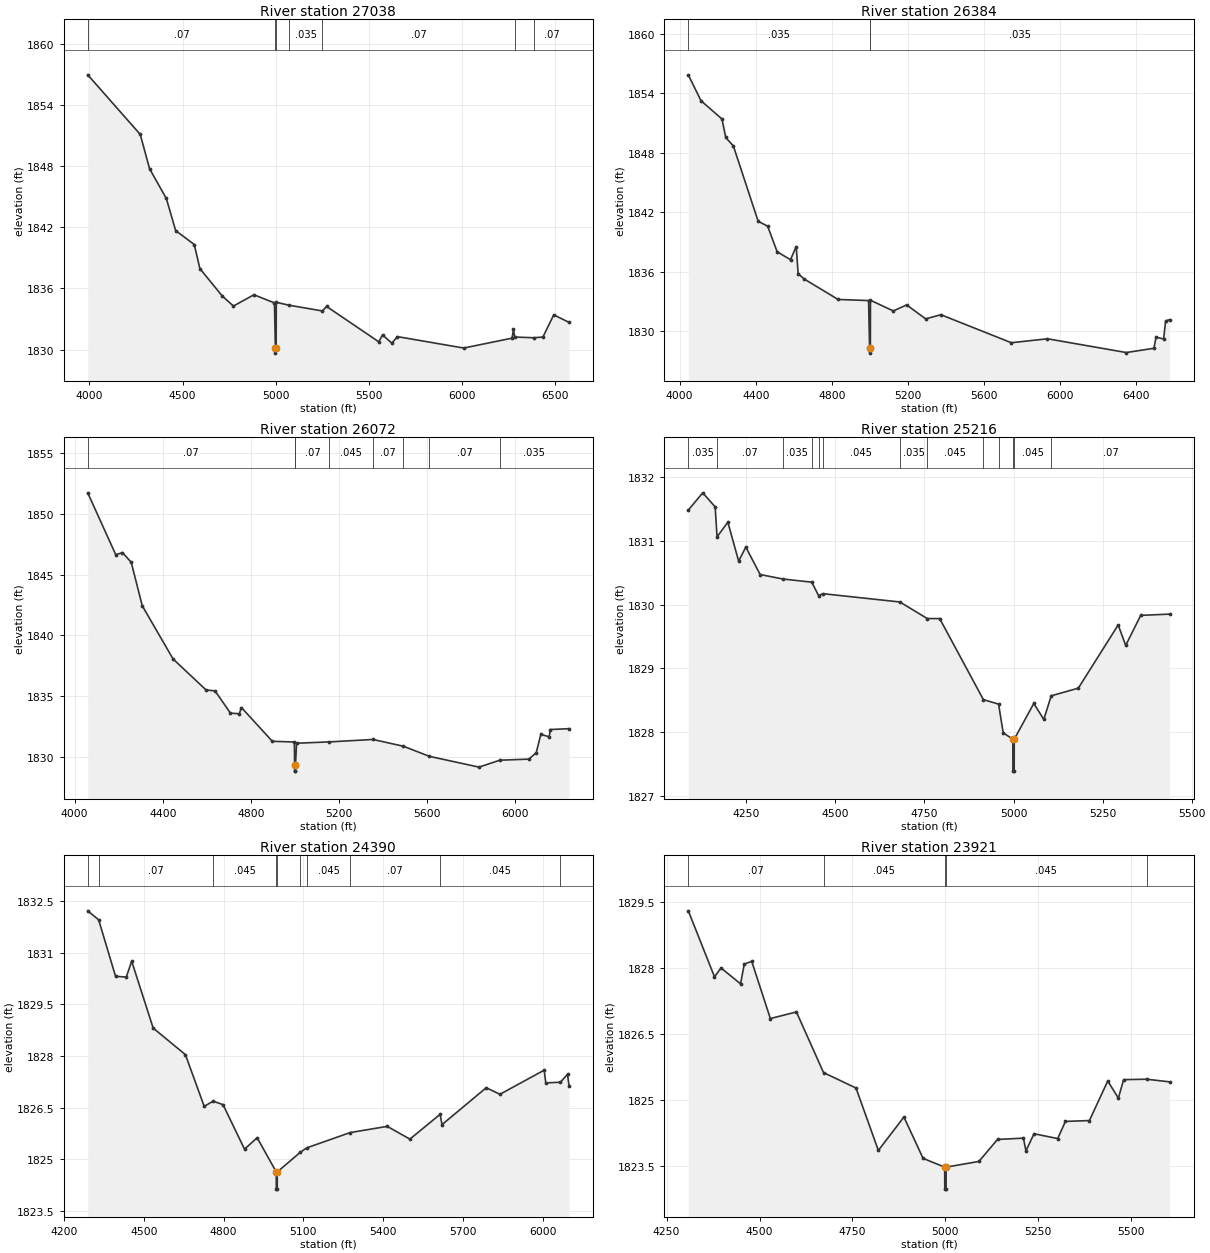
Type RM Length L Ch R = 1,27038,654,654,654
BEGIN DESCRIPTION:
Elm 01 14 2.0
END DESCRIPTION:
XS GIS Cut Line= 3
      1559283.24      6812941.87      1561283.36      6812921.74
      1561614.37      6812442.82
#Sta/Elev= 30
  3991.0 1856.97  4272.8 1851.12  4322.8 1847.75  4412.8 1844.83  4462.8 1841.68
  4562.8 1840.31  4592.8 1837.95  4712.8 1835.26  4772.8 1834.27  4882.8 1835.38
  4992.8 1834.58  4998.0 1830.15  4998.3 1829.65  5002.0 1830.15  5002.8 1834.64
  5072.1 1834.35  5250.5 1833.79  5272.8 1834.23  5552.8 1830.76  5572.8 1831.44
  5622.8 1830.63  5652.8 1831.27  6008.5 1830.15  6268.0 1831.12  6275.4 1831.97
  6282.1 1831.23  6384.4 1831.16  6433.4 1831.23  6491.7 1833.41  6573.4 1832.67
#Mann=7,-1,0
  3991.0    0.07       0  4998.0    0.07       0  5002.0    0.07       0
  5072.1   0.035       0  5250.5    0.07       0  6282.1    0.16       0
  6384.4    0.07       0
Bank Sta=4998,5002
Exp/Cntr=0.3,0.1

Type RM Length L Ch R = 1,26384,312,312,312
BEGIN DESCRIPTION:
Elm 01 14 1.0
END DESCRIPTION:
XS GIS Cut Line= 3
      1559308.16      6813591.69      1561308.24      6813571.57
      1561825.35      6813678.35
#Sta/Elev= 30
  4045.6 1855.88  4112.4 1853.26  4222.4 1851.42  4242.4 1849.55  4282.4 1848.69
  4412.5 1841.09  4462.5 1840.59  4512.5 1838.00  4582.5 1837.21  4612.5 1838.54
  4622.5 1835.81  4652.5 1835.28  4832.5 1833.19  4992.5 1833.08  4998.0 1828.27
  4998.3 1827.77  5002.0 1828.27  5002.5 1833.11  5122.5 1832.03  5192.5 1832.64
  5292.5 1831.23  5372.5 1831.65  5742.5 1828.82  5932.5 1829.22  6346.6 1827.83
  6491.8 1828.26  6502.5 1829.38  6542.5 1829.20  6553.0 1831.02  6573.8 1831.15
#Mann=3,-1,0
  4045.6   0.035       0  4998.0   0.035       0  5002.0   0.035       0
Bank Sta=4998,5002
Exp/Cntr=0.3,0.1

Type RM Length L Ch R = 1,26072,856,856,856
BEGIN DESCRIPTION:
Elm 01 17 32.0
END DESCRIPTION:
XS GIS Cut Line= 4
      1559327.62      6813881.90      1560090.46      6813894.56
      1560638.86      6813895.09      1561489.77      6813703.76
#Sta/Elev= 30
  4059.5 1851.75  4186.9 1846.64  4216.9 1846.83  4256.9 1846.02  4306.9 1842.44
  4446.9 1838.05  4597.0 1835.49  4637.0 1835.43  4707.0 1833.59  4747.0 1833.54
  4757.0 1834.05  4897.0 1831.27  4997.0 1831.21  4998.0 1829.31  4998.3 1828.81
  5001.8 1828.81  5002.0 1829.31  5007.0 1831.11  5155.8 1831.22  5353.8 1831.42
  5491.9 1830.86  5609.4 1830.03  5834.7 1829.14  5928.9 1829.71  6061.4 1829.80
  6094.6 1830.34  6115.1 1831.84  6153.1 1831.64  6158.3 1832.24  6243.0 1832.31
#Mann=8,-1,0
  4059.5    0.07       0  4998.0    0.07       0  5002.0    0.07       0
  5155.8   0.045       0  5353.8    0.07       0  5491.9   0.045       0
  5609.4    0.07       0  5928.9   0.035       0
Bank Sta=4998,5002
Exp/Cntr=0.3,0.1

Type RM Length L Ch R = 1,25216,826,826,826
BEGIN DESCRIPTION:
Elm 01 17 31.0
END DESCRIPTION:
XS GIS Cut Line= 3
      1559944.82      6814552.25      1561014.52      6814419.33
      1561105.27      6814161.88
#Sta/Elev= 30
  4087.1 1831.48  4127.6 1831.75  4162.5 1831.53  4167.8 1831.06  4198.1 1831.29
  4228.4 1830.68  4248.5 1830.90  4288.8 1830.47  4352.6 1830.40  4433.8 1830.35
  4452.7 1830.14  4464.9 1830.17  4680.9 1830.04  4758.0 1829.78  4792.7 1829.78
  4915.4 1828.51  4958.0 1828.44  4971.0 1827.99  4998.0 1827.89  4998.3 1827.39
  5001.8 1827.39  5002.0 1827.89  5056.9 1828.45  5084.9 1828.20  5105.8 1828.57
  5181.9 1828.69  5293.7 1829.68  5314.9 1829.36  5357.0 1829.83  5438.0 1829.85
#Mann=13,-1,0
  4087.1   0.035       0  4167.8    0.07       0  4352.6   0.035       0
  4433.8   0.045       0  4452.7   0.035       0  4464.9   0.045       0
  4680.9   0.035       0  4758.0   0.045       0  4915.4   0.035       0
  4958.0   0.045       0  4998.0   0.045       0  5002.0   0.045       0
  5105.8    0.07       0
Bank Sta=4998,5002
Exp/Cntr=0.3,0.1

Type RM Length L Ch R = 1,24390,469,469,469
BEGIN DESCRIPTION:
Elm 01 17 30.0
END DESCRIPTION:
XS GIS Cut Line= 4
      1559801.37      6815063.11      1560428.54      6815153.90
      1560993.76      6815062.21      1561320.26      6814554.20
#Sta/Elev= 30
  4289.0 1832.21  4330.1 1831.95  4393.7 1830.31  4434.1 1830.29  4454.3 1830.75
  4535.2 1828.81  4656.4 1828.04  4727.1 1826.54  4760.5 1826.69  4797.9 1826.59
  4878.7 1825.30  4926.3 1825.63  4998.0 1824.64  4998.3 1824.14  5001.8 1824.14
  5002.0 1824.64  5088.9 1825.21  5113.8 1825.34  5276.2 1825.78  5415.5 1825.96
  5500.8 1825.59  5614.4 1826.31  5621.5 1826.01  5787.9 1827.08  5839.4 1826.89
  6005.9 1827.59  6011.8 1827.22  6066.8 1827.24  6093.7 1827.47  6099.2 1827.14
#Mann=10,-1,0
  4289.0   0.035       0  4330.1    0.07       0  4760.5   0.045       0
  4998.0   0.045       0  5002.0   0.045       0  5088.9   0.035       0
  5113.8   0.045       0  5276.2    0.07       0  5614.4   0.045       0
  6066.8    0.07       0
Bank Sta=4998,5002
Exp/Cntr=0.3,0.1

Type RM Length L Ch R = 1,23921,477,477,477
BEGIN DESCRIPTION:
Elm 01 17 29.0
END DESCRIPTION:
XS GIS Cut Line= 3
      1559894.71      6815477.47      1560741.89      6815529.14
      1561077.15      6815235.23
#Sta/Elev= 30
  4308.4 1829.31  4378.8 1827.81  4396.5 1828.01  4448.9 1827.65  4459.0 1828.10
  4479.0 1828.16  4529.1 1826.86  4599.2 1827.01  4672.2 1825.63  4759.5 1825.28
  4819.6 1823.86  4888.4 1824.62  4939.9 1823.68  4998.0 1823.48  4998.3 1822.98
  5001.8 1822.98  5002.0 1823.48  5090.1 1823.61  5140.2 1824.11  5209.9 1824.14
  5216.6 1823.85  5238.4 1824.24  5302.0 1824.13  5322.8 1824.52  5387.4 1824.54
  5436.7 1825.44  5465.2 1825.05  5479.4 1825.47  5541.1 1825.48  5603.0 1825.42
#Mann=5,-1,0
  4308.4    0.07       0  4672.2   0.045       0  4998.0   0.045       0
  5002.0   0.045       0  5541.1    0.07       0
Bank Sta=4998,5002
Exp/Cntr=0.3,0.1

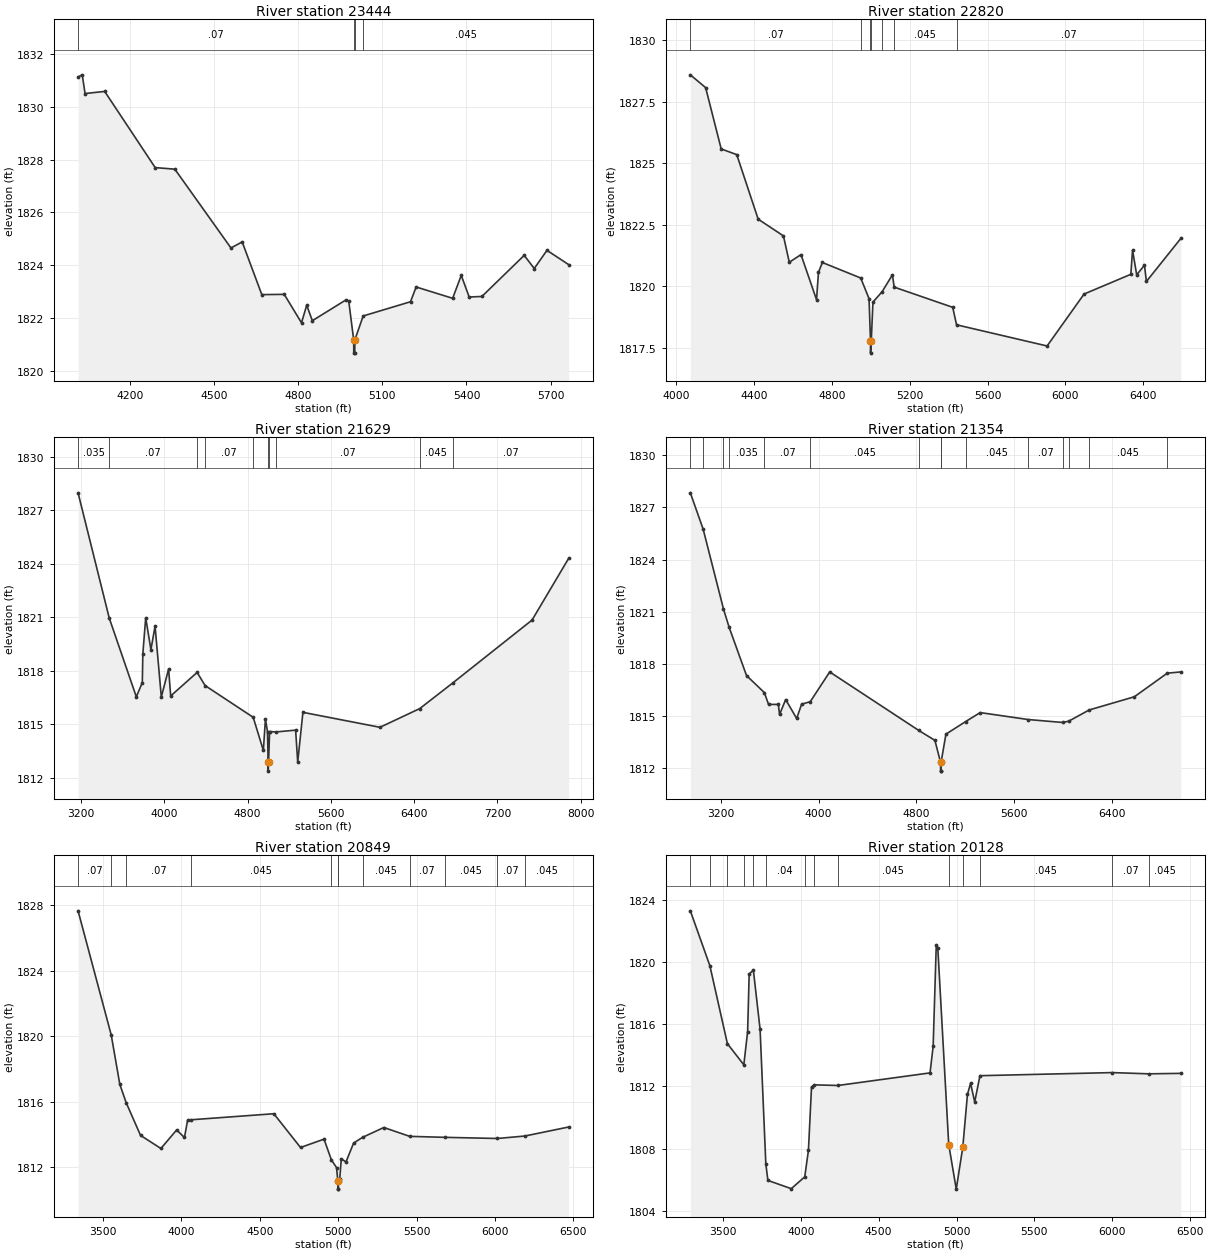
Type RM Length L Ch R = 1,23444,624,624,624
BEGIN DESCRIPTION:
Elm 01 17 28.4
END DESCRIPTION:
XS GIS Cut Line= 3
      1559720.09      6815962.74      1560985.02      6815931.25
      1561194.37      6815495.22
#Sta/Elev= 30
  4015.3 1831.14  4030.2 1831.22  4040.2 1830.51  4110.2 1830.59  4290.3 1827.70
  4360.3 1827.64  4560.4 1824.65  4600.4 1824.88  4670.4 1822.88  4750.4 1822.89
  4811.9 1821.81  4830.5 1822.48  4850.5 1821.89  4970.5 1822.68  4980.5 1822.62
  4998.0 1821.16  4998.3 1820.66  5001.8 1820.66  5002.0 1821.16  5031.8 1822.07
  5200.6 1822.61  5220.6 1823.17  5350.8 1822.74  5381.5 1823.61  5409.7 1822.79
  5455.0 1822.81  5605.9 1824.37  5641.7 1823.87  5687.0 1824.56  5764.3 1824.02
#Mann=4,-1,0
  4015.3    0.07       0  4998.0    0.07       0  5002.0    0.07       0
  5031.8   0.045       0
Bank Sta=4998,5002
Exp/Cntr=0.3,0.1

Type RM Length L Ch R = 1,22820,1191,1191,1191
BEGIN DESCRIPTION:
Elm 01 17 28.2
END DESCRIPTION:
XS GIS Cut Line= 4
      1559776.35      6816580.16      1561252.92      6816551.20
      1561459.49      6816527.02      1561502.60      6815691.07
#Sta/Elev= 30
  4071.8 1828.59  4150.5 1828.07  4230.5 1825.58  4310.5 1825.35  4420.5 1822.73
  4550.5 1822.05  4580.5 1820.98  4640.6 1821.29  4720.6 1819.46  4730.6 1820.57
  4750.6 1820.97  4947.8 1820.34  4990.6 1819.50  4998.0 1817.79  4998.3 1817.29
  5002.0 1817.79  5010.6 1819.36  5058.3 1819.79  5110.7 1820.47  5119.8 1819.97
  5420.7 1819.15  5440.4 1818.44  5905.9 1817.58  6096.1 1819.69  6336.4 1820.49
  6345.2 1821.47  6366.5 1820.47  6406.5 1820.86  6416.5 1820.20  6593.7 1821.95
#Mann=7,-1,0
  4071.8    0.07       0  4947.8   0.035       0  4998.0   0.035       0
  5002.0   0.035       0  5058.3    0.07       0  5119.8   0.045       0
  5440.4    0.07       0
Bank Sta=4998,5002
Exp/Cntr=0.3,0.1

Type RM Length L Ch R = 1,21629,275,275,275
BEGIN DESCRIPTION:
Elm 01 17 28.0
END DESCRIPTION:
XS GIS Cut Line= 3
      1559805.49      6817140.78      1562688.28      6817104.58
      1564132.22      6815982.15
#Sta/Elev= 30
  3172.2 1827.99  3471.6 1820.96  3731.8 1816.54  3789.3 1817.34  3794.3 1818.95
  3821.8 1820.98  3871.8 1819.19  3911.8 1820.50  3971.8 1816.53  4041.8 1818.10
  4061.8 1816.59  4315.6 1817.91  4392.8 1817.17  4854.5 1815.39  4951.8 1813.53
  4971.9 1815.29  4991.9 1814.58  4998.0 1812.87  4998.3 1812.37  5002.0 1812.87
  5011.9 1814.59  5074.7 1814.57  5261.9 1814.67  5281.9 1812.87  5331.9 1815.67
  6072.1 1814.83  6454.0 1815.88  6773.6 1817.33  7533.0 1820.85  7884.1 1824.31
#Mann=10,-1,0
  3172.2   0.035       0  3471.6    0.07       0  4315.6   0.045       0
  4392.8    0.07       0  4854.5    0.16       0  4998.0    0.07       0
  5002.0    0.16       0  5074.7    0.07       0  6454.0   0.045       0
  6773.6    0.07       0
Bank Sta=4998,5002
Exp/Cntr=0.3,0.1

Type RM Length L Ch R = 1,21354,505,505,505
BEGIN DESCRIPTION:
Elm 01 17 27.0
END DESCRIPTION:
XS GIS Cut Line= 3
      1559785.62      6817317.64      1562606.28      6817245.86
      1563795.46      6817213.41
#Sta/Elev= 30
  2951.8 1827.84  3057.0 1825.74  3222.6 1821.16  3269.0 1820.10  3411.3 1817.32
  3557.2 1816.34  3591.4 1815.66  3671.4 1815.66  3681.4 1815.08  3731.4 1815.94
  3821.5 1814.85  3861.5 1815.67  3932.7 1815.82  4091.6 1817.53  4820.1 1814.16
  4951.8 1813.59  4998.0 1812.32  4998.3 1811.82  5001.8 1811.82  5002.0 1812.32
  5041.9 1813.95  5202.2 1814.67  5321.9 1815.19  5714.1 1814.79  5998.1 1814.62
  6047.0 1814.70  6212.8 1815.34  6582.4 1816.10  6851.8 1817.46  6963.0 1817.53
#Mann=15,-1,0
  2951.8    0.07       0  3057.0   0.035       0  3222.6    0.07       0
  3269.0   0.035       0  3557.2    0.07       0  3932.7   0.045       0
  4820.1    0.07       0  4998.0    0.07       0  5002.0    0.07       0
  5202.2   0.045       0  5714.1    0.07       0  5998.1   0.045       0
  6047.0    0.07       0  6212.8   0.045       0  6851.8    0.07       0
Bank Sta=4998,5002
Exp/Cntr=0.3,0.1

Type RM Length L Ch R = 1,20849,721,721,721
BEGIN DESCRIPTION:
Elm 01 17 26.0
END DESCRIPTION:
XS GIS Cut Line= 3
      1559996.72      6817626.64      1561716.61      6817667.35
      1563116.65      6817514.77
#Sta/Elev= 30
  3341.5 1827.66  3553.1 1820.08  3607.6 1817.08  3648.0 1815.96  3739.9 1813.96
  3869.9 1813.16  3970.0 1814.29  4020.0 1813.83  4040.0 1814.88  4060.8 1814.91
  4590.1 1815.28  4760.2 1813.22  4910.2 1813.73  4956.9 1812.47  4990.2 1811.99
  4998.0 1811.18  4998.3 1810.68  5001.8 1810.68  5002.0 1811.18  5010.2 1811.29
  5020.3 1812.53  5050.3 1812.34  5098.8 1813.49  5156.0 1813.84  5291.7 1814.44
  5456.3 1813.90  5680.2 1813.84  6015.2 1813.77  6191.3 1813.92  6470.2 1814.47
#Mann=12,-1,0
  3341.5    0.07       0  3553.1   0.035       0  3648.0    0.07       0
  4060.8   0.045       0  4956.9    0.07       0  4998.0    0.07       0
  5002.0    0.07       0  5156.0   0.045       0  5456.3    0.07       0
  5680.2   0.045       0  6015.2    0.07       0  6191.3   0.045       0
Bank Sta=4998,5002
Exp/Cntr=0.3,0.1

Type RM Length L Ch R = 1,20128,557,557,557
BEGIN DESCRIPTION:
Elm 01 17 25.0
END DESCRIPTION:
XS GIS Cut Line= 3
      1559847.51      6818376.50      1561658.12      6818275.82
      1562971.57      6818020.71
#Sta/Elev= 30
  3290.0 1823.30  3415.5 1819.77  3528.1 1814.75  3633.7 1813.39  3658.1 1815.53
  3668.1 1819.24  3695.0 1819.48  3738.2 1815.67  3775.0 1807.02  3788.3 1805.95
  3938.5 1805.42  4025.0 1806.18  4048.7 1807.88  4068.6 1811.97  4087.2 1812.10
  4238.4 1812.06  4829.9 1812.87  4849.9 1814.58  4869.9 1821.09  4879.9 1820.89
  4950.0 1808.26  4998.3 1805.39  5040.2 1808.08  5070.2 1811.48  5090.3 1812.20
  5116.9 1811.00  5150.6 1812.69  6000.4 1812.89  6234.3 1812.81  6441.4 1812.84
#Mann=14,-1,0
  3290.0    0.07       0  3415.5   0.035       0  3528.1    0.07       0
  3633.7   0.035       0  3695.0    0.07       0  3775.0    0.04       0
  4025.0    0.07       0  4087.2   0.035       0  4238.4   0.045       0
  4950.0    0.04       0  5040.2   0.045       0  5150.6   0.045       0
  6000.4    0.07       0  6234.3   0.045       0
Bank Sta=4950,5040.2
Exp/Cntr=0.3,0.1

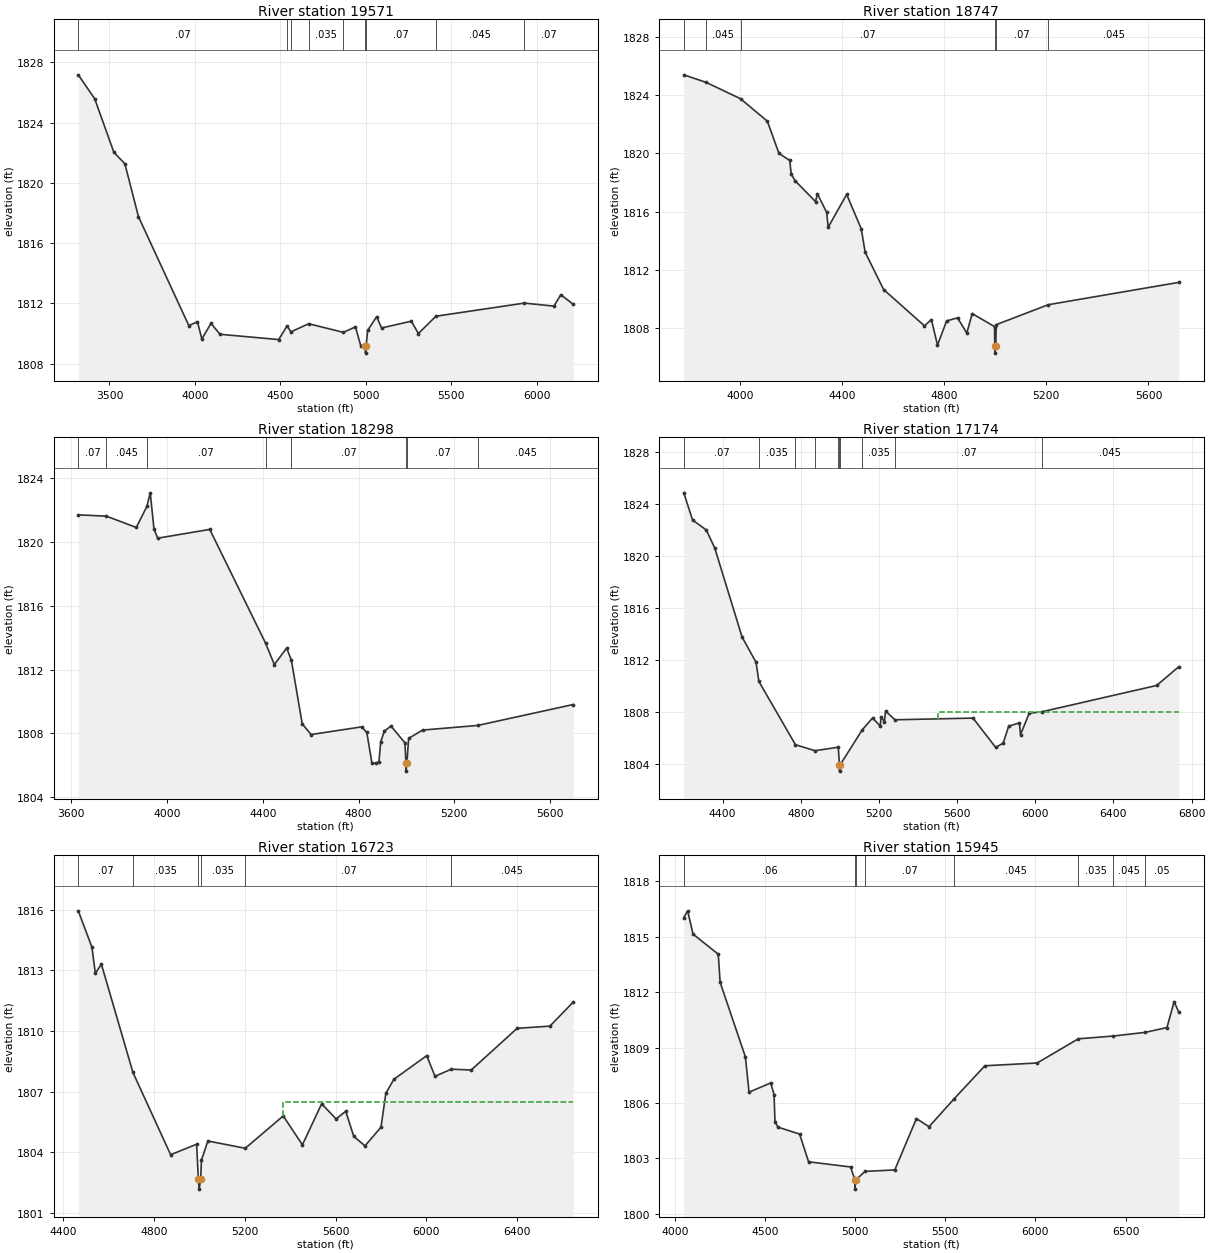
Type RM Length L Ch R = 1,19571,824,824,824
BEGIN DESCRIPTION:
Elm 01 17 24.5
END DESCRIPTION:
XS GIS Cut Line= 3
      1559948.57      6819050.49      1561787.14      6818720.92
      1562780.01      6818453.98
#Sta/Elev= 30
  3317.8 1827.17  3413.8 1825.58  3526.3 1822.02  3590.2 1821.27  3669.8 1817.76
  3964.4 1810.53  4015.2 1810.78  4040.5 1809.64  4094.2 1810.67  4147.2 1809.95
  4490.7 1809.60  4539.2 1810.51  4561.6 1810.11  4666.0 1810.65  4868.2 1810.08
  4939.7 1810.44  4970.2 1809.20  4998.0 1809.20  4998.3 1808.70  5002.0 1809.20
  5010.8 1810.21  5063.6 1811.12  5092.1 1810.37  5266.3 1810.82  5307.7 1810.00
  5410.4 1811.15  5927.6 1812.02  6101.0 1811.82  6140.9 1812.58  6213.8 1811.94
#Mann=9,-1,0
  3317.8    0.07       0  4539.2   0.035       0  4561.6    0.07       0
  4666.0   0.035       0  4868.2    0.07       0  4998.0    0.07       0
  5002.0    0.07       0  5410.4   0.045       0  5927.6    0.07       0
Bank Sta=4998,5002
Exp/Cntr=0.3,0.1

Type RM Length L Ch R = 1,18747,449,449,449
BEGIN DESCRIPTION:
Elm 01 17 24.0
END DESCRIPTION:
XS GIS Cut Line= 3
      1560833.01      6819890.06      1561854.63      6819222.66
      1562420.41      6818779.62
#Sta/Elev= 30
  3779.7 1825.39  3867.5 1824.87  4002.0 1823.75  4107.0 1822.21  4152.3 1820.01
  4194.5 1819.52  4200.5 1818.59  4215.6 1818.13  4295.7 1816.70  4303.1 1817.23
  4339.3 1815.96  4345.3 1814.94  4417.7 1817.19  4475.0 1814.82  4490.1 1813.23
  4562.5 1810.67  4722.4 1808.18  4749.6 1808.61  4773.5 1806.86  4809.3 1808.52
  4852.1 1808.73  4888.3 1807.68  4909.4 1809.02  4996.9 1808.13  4998.0 1806.81
  4998.3 1806.31  5002.0 1806.81  5003.4 1808.26  5207.5 1809.63  5718.6 1811.16
#Mann=6,-1,0
  3779.7    0.07       0  3867.5   0.045       0  4002.0    0.07       0
  4998.0    0.07       0  5002.0    0.07       0  5207.5   0.045       0
Bank Sta=4998,5002
Exp/Cntr=0.3,0.1

Type RM Length L Ch R = 1,18298,1124,1124,1124
BEGIN DESCRIPTION:
Elm 01 17 23.0
END DESCRIPTION:
XS GIS Cut Line= 3
      1560779.46      6820306.28      1562084.69      6819519.43
      1562558.90      6819253.79
#Sta/Elev= 30
  3629.3 1821.68  3746.8 1821.60  3871.6 1820.89  3915.8 1822.21  3929.9 1823.06
  3945.4 1820.81  3960.9 1820.22  4178.4 1820.77  4412.0 1813.64  4448.2 1812.31
  4499.8 1813.34  4519.5 1812.58  4564.7 1808.60  4601.6 1807.93  4813.2 1808.41
  4834.6 1808.06  4855.9 1806.14  4871.5 1806.14  4885.2 1806.22  4892.8 1807.49
  4908.3 1808.15  4935.5 1808.46  4993.8 1807.41  4998.0 1806.14  4998.3 1805.64
  5002.0 1806.14  5009.3 1807.69  5067.6 1808.21  5297.9 1808.50  5696.9 1809.81
#Mann=8,-1,0
  3629.3    0.07       0  3746.8   0.045       0  3915.8    0.07       0
  4412.0   0.035       0  4519.5    0.07       0  4998.0    0.07       0
  5002.0    0.07       0  5297.9   0.045       0
Bank Sta=4998,5002
Exp/Cntr=0.3,0.1

Type RM Length L Ch R = 1,17174,451,451,451
BEGIN DESCRIPTION:
Elm 01 17 22.0
END DESCRIPTION:
XS GIS Cut Line= 4
      1561287.80      6820809.22      1562006.76      6820525.83
      1562059.33      6820478.24      1563557.93      6819699.43
#Sta/Elev= 30
  4201.5 1824.89  4246.3 1822.80  4316.7 1822.03  4360.0 1820.64  4499.5 1813.80
  4571.2 1811.85  4585.6 1810.38  4772.9 1805.51  4872.8 1805.05  4991.8 1805.32
  4998.0 1803.98  4998.3 1803.48  5002.1 1803.98  5114.3 1806.65  5167.5 1807.57
  5206.1 1806.95  5211.7 1807.63  5228.2 1807.29  5233.8 1808.11  5281.7 1807.43
  5681.3 1807.56  5797.5 1805.30  5836.0 1805.64  5863.8 1806.94  5918.9 1807.19
  5924.5 1806.29  5968.7 1807.93  6034.9 1808.05  6620.8 1810.07  6734.1 1811.51
#Mann=10,-1,0
  4201.5    0.07       0  4585.6   0.035       0  4772.9    0.07       0
  4872.8   0.035       0  4991.8    0.07       0  4998.0    0.07       0
  5002.1    0.07       0  5114.3   0.035       0  5281.7    0.07       0
  6034.9   0.045       0
#XS Ineff=2,0
       0                 5500.00    0.00 1808.00
Permanent Ineff=
       F       F
Bank Sta=4998,5002.1
Exp/Cntr=0.3,0.1

Type RM Length L Ch R = 1,16723,778,778,778
BEGIN DESCRIPTION:
Elm 01 17 21.0
END DESCRIPTION:
XS GIS Cut Line= 4
      1561827.79      6820996.12      1562277.91      6820849.27
      1562890.97      6820209.21      1563581.30      6819760.52
#Sta/Elev= 30
  4465.3 1815.94  4525.5 1814.14  4540.5 1812.85  4567.2 1813.30  4706.3 1807.95
  4872.6 1803.88  4987.1 1804.40  4995.0 1802.68  4998.2 1802.18  5005.1 1802.68
  5008.5 1803.61  5036.8 1804.56  5201.9 1804.20  5369.2 1805.80  5453.8 1804.37
  5538.7 1806.40  5602.5 1805.65  5645.0 1806.03  5680.2 1804.79  5729.8 1804.32
  5800.4 1805.24  5821.7 1806.91  5857.2 1807.61  6002.2 1808.78  6038.4 1807.76
  6110.9 1808.11  6198.5 1808.07  6400.8 1810.13  6545.5 1810.24  6648.4 1811.43
#Mann=6,-1,0
  4465.3    0.07       0  4706.3   0.035       0  4995.0   0.035       0
  5005.1   0.035       0  5201.9    0.07       0  6110.9   0.045       0
#XS Ineff=2,0
       0                 5369.00    0.00 1806.50
Permanent Ineff=
       F       F
Bank Sta=4995,5005.1
Exp/Cntr=0.3,0.1

Type RM Length L Ch R = 1,15945,328,328,328
BEGIN DESCRIPTION:
Elm 01 17 20.0
END DESCRIPTION:
XS GIS Cut Line= 4
      1561903.80      6821055.71      1562827.62      6820995.72
      1562888.26      6820945.89      1564630.61      6820908.66
#Sta/Elev= 30
  4048.2 1816.04  4069.4 1816.41  4099.5 1815.15  4239.5 1814.06  4249.8 1812.54
  4390.1 1808.50  4410.2 1806.59  4530.4 1807.09  4549.2 1806.46  4554.2 1805.00
  4570.5 1804.70  4690.8 1804.32  4740.9 1802.82  4974.0 1802.54  4997.6 1801.84
  4997.9 1801.34  5002.5 1801.84  5053.9 1802.30  5219.2 1802.38  5339.3 1805.16
  5409.3 1804.72  5549.3 1806.24  5719.3 1808.02  6009.4 1808.17  6237.6 1809.48
  6431.9 1809.63  6609.8 1809.83  6729.6 1810.09  6769.6 1811.49  6795.2 1810.92
#Mann=8,-1,0
  4048.2    0.06       0  4997.6   0.035       0  5002.5   0.035       0
  5053.9    0.07       0  5549.3   0.045       0  6237.6   0.035       0
  6431.9   0.045       0  6609.8    0.05       0
Bank Sta=4997.6,5002.5
Exp/Cntr=0.3,0.1

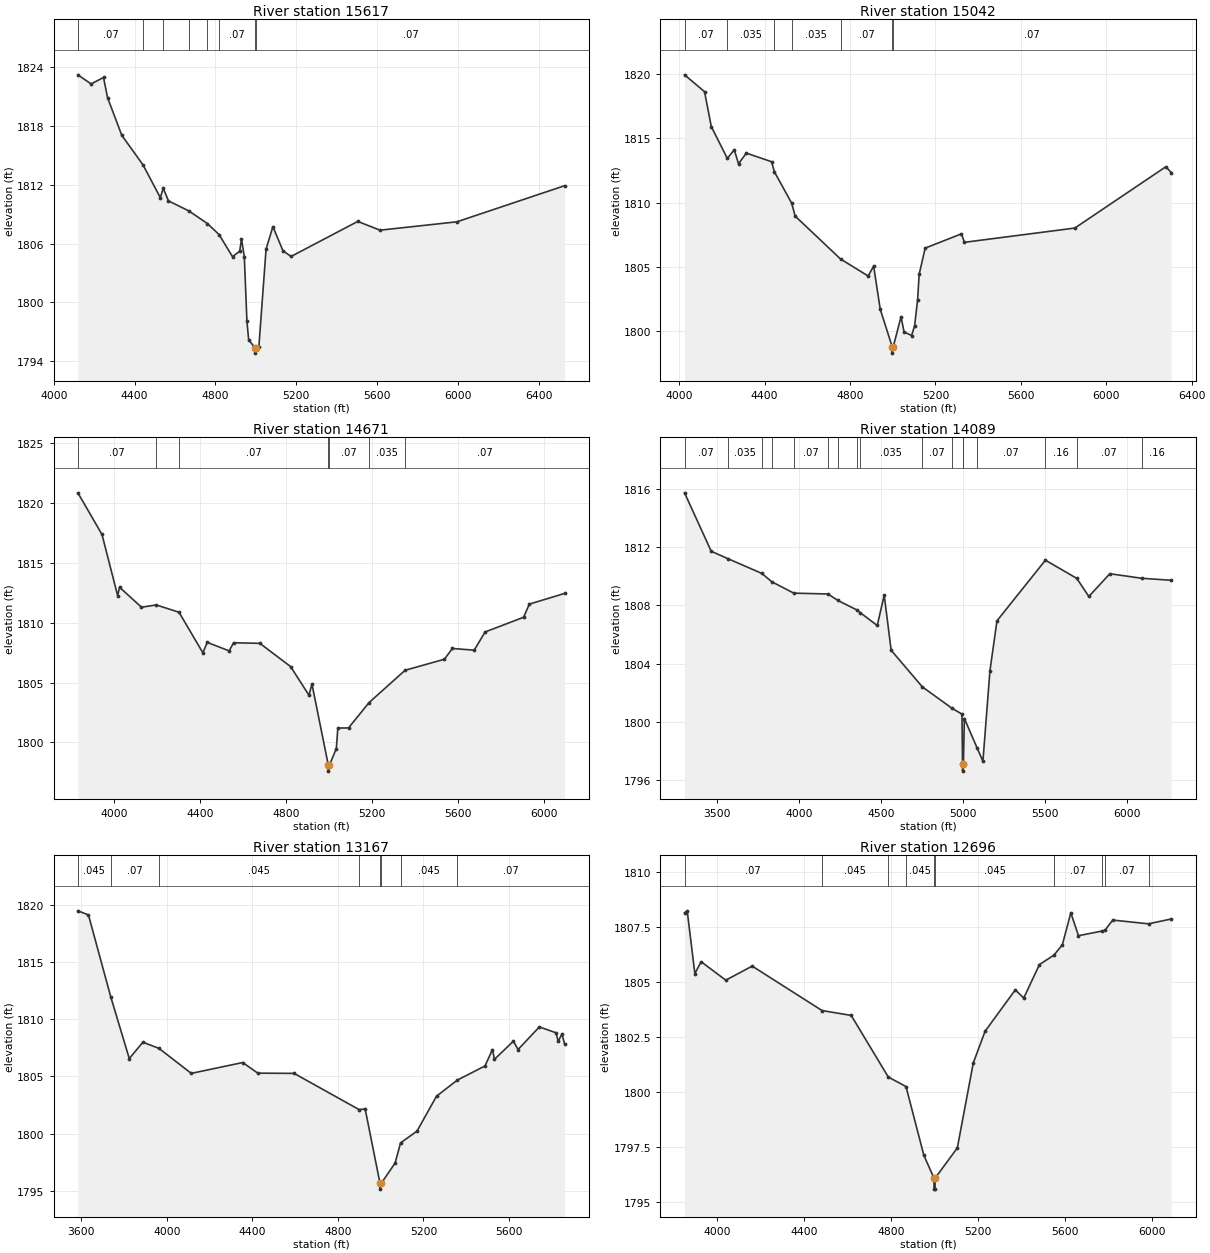
Type RM Length L Ch R = 1,15617,575,575,575
BEGIN DESCRIPTION:
Elm 01 17 19.0
END DESCRIPTION:
XS GIS Cut Line= 4
      1562168.65      6821419.57      1562856.08      6821354.47
      1563059.52      6821210.28      1564528.06      6821156.06
#Sta/Elev= 30
  4119.1 1823.19  4184.7 1822.26  4246.0 1822.92  4266.1 1820.86  4336.4 1817.03
  4442.0 1814.00  4527.3 1810.67  4541.7 1811.64  4567.4 1810.35  4669.5 1809.31
  4760.6 1808.03  4818.1 1806.91  4884.6 1804.66  4920.3 1805.22  4929.0 1806.47
  4943.1 1804.65  4956.0 1798.10  4964.6 1796.19  4997.5 1795.33  4997.9 1794.83
  5002.6 1795.33  5015.1 1795.48  5050.8 1805.43  5084.5 1807.72  5134.5 1805.26
  5174.5 1804.68  5504.7 1808.25  5614.8 1807.36  5995.1 1808.21  6528.5 1811.89
#Mann=8,-1,0
  4119.1    0.07       0  4442.0   0.063       0  4541.7   0.035       0
  4669.5    0.07       0  4760.6   0.035       0  4818.1    0.07       0
  4997.5    0.07       0  5002.6    0.07       0
Bank Sta=4997.5,5002.6
Exp/Cntr=0.3,0.1

Type RM Length L Ch R = 1,15042,371,371,371
BEGIN DESCRIPTION:
Elm 01 17 18.0
END DESCRIPTION:
XS GIS Cut Line= 4
      1562386.81      6821939.67      1563305.58      6821613.65
      1563598.32      6821323.53      1564488.31      6821261.47
#Sta/Elev= 30
  4025.1 1819.95  4118.7 1818.64  4150.5 1815.92  4225.4 1813.45  4258.1 1814.12
  4277.8 1813.03  4314.6 1813.86  4432.7 1813.19  4445.8 1812.41  4527.0 1809.96
  4543.1 1808.96  4755.8 1805.62  4885.1 1804.30  4910.7 1805.07  4941.6 1801.71
  4997.5 1798.80  4997.9 1798.30  5002.6 1798.80  5039.0 1801.13  5053.1 1799.95
  5088.4 1799.67  5102.6 1800.43  5116.7 1802.47  5123.8 1804.43  5152.1 1806.47
  5321.8 1807.58  5335.9 1806.92  5852.9 1808.03  6279.1 1812.80  6304.3 1812.35
#Mann=7,-1,0
  4025.1    0.07       0  4225.4   0.035       0  4445.8    0.07       0
  4527.0   0.035       0  4755.8    0.07       0  4997.5    0.07       0
  5002.6    0.07       0
Bank Sta=4997.5,5002.6
Exp/Cntr=0.3,0.1

Type RM Length L Ch R = 1,14671,582,582,582
BEGIN DESCRIPTION:
Elm 01 17 17.0
END DESCRIPTION:
XS GIS Cut Line= 4
      1562404.99      6822188.00      1563423.32      6821987.29
      1563780.45      6821647.88      1564476.62      6821423.00
#Sta/Elev= 30
  3833.3 1820.86  3945.4 1817.38  4018.1 1812.27  4027.0 1812.97  4128.9 1811.30
  4197.6 1811.49  4303.4 1810.88  4414.3 1807.49  4434.7 1808.36  4536.6 1807.65
  4557.0 1808.33  4679.3 1808.28  4822.0 1806.34  4907.3 1803.95  4921.4 1804.87
  4997.4 1798.10  4997.8 1797.60  5002.6 1798.10  5034.7 1799.49  5041.6 1801.20
  5091.3 1801.21  5186.7 1803.33  5354.5 1806.03  5536.8 1806.95  5574.3 1807.85
  5675.6 1807.71  5726.0 1809.23  5905.1 1810.46  5931.9 1811.56  6095.5 1812.45
#Mann=7,-1,0
  3833.3    0.07       0  4197.6   0.035       0  4303.4    0.07       0
  4997.4    0.07       0  5002.6    0.07       0  5186.7   0.035       0
  5354.5    0.07       0
Bank Sta=4997.4,5002.6
Exp/Cntr=0.3,0.1

Type RM Length L Ch R = 1,14089,922,922,922
BEGIN DESCRIPTION:
Elm 01 17 16.0
END DESCRIPTION:
XS GIS Cut Line= 3
      1562804.97      6823388.03      1563997.19      6822181.79
      1564958.21      6821353.52
#Sta/Elev= 30
  3304.0 1815.71  3466.7 1811.70  3567.0 1811.20  3775.4 1810.18  3835.2 1809.61
  3969.3 1808.83  4178.1 1808.77  4237.4 1808.33  4355.1 1807.67  4375.3 1807.48
  4477.9 1806.61  4520.3 1808.69  4562.7 1804.91  4752.5 1802.40  4934.8 1800.92
  4994.0 1800.53  4997.4 1797.12  4997.8 1796.62  5002.7 1797.12  5008.6 1800.23
  5085.5 1798.23  5121.6 1797.30  5164.4 1803.51  5207.2 1806.93  5502.3 1811.09
  5693.5 1809.84  5766.7 1808.60  5894.8 1810.16  6088.0 1809.85  6268.7 1809.71
#Mann=17,-1,0
  3304.0    0.07       0  3567.0   0.035       0  3775.4    0.07       0
  3835.2   0.045       0  3969.3    0.07       0  4178.1   0.045       0
  4237.4   0.035       0  4355.1   0.045       0  4375.3   0.035       0
  4752.5    0.07       0  4934.8    0.16       0  4997.4    0.07       0
  5002.7    0.16       0  5085.5    0.07       0  5502.3    0.16       0
  5693.5    0.07       0  6088.0    0.16       0
Bank Sta=4997.4,5002.7
Exp/Cntr=0.3,0.1

Type RM Length L Ch R = 1,13167,471,471,471
BEGIN DESCRIPTION:
Elm 01 17 15.0
END DESCRIPTION:
XS GIS Cut Line= 3
      1563304.97      6823888.03      1564298.96      6822879.82
      1564664.94      6822101.25
#Sta/Elev= 30
  3584.2 1819.51  3633.7 1819.15  3738.0 1811.97  3824.6 1806.57  3888.3 1808.00
  3963.5 1807.46  4114.6 1805.27  4355.0 1806.22  4425.8 1805.29  4595.4 1805.27
  4899.0 1802.10  4927.8 1802.15  4997.3 1795.63  4997.7 1795.13  5002.8 1795.63
  5067.9 1797.42  5093.3 1799.18  5170.1 1800.21  5261.4 1803.27  5358.7 1804.68
  5488.2 1805.92  5523.2 1807.36  5532.4 1806.50  5620.8 1808.09  5642.9 1807.36
  5742.3 1809.34  5819.7 1808.83  5830.7 1808.09  5848.0 1808.71  5860.3 1807.87
#Mann=8,-1,0
  3584.2   0.045       0  3738.0    0.07       0  3963.5   0.045       0
  4899.0    0.07       0  4997.3    0.07       0  5002.8    0.07       0
  5093.3   0.045       0  5358.7    0.07       0
Bank Sta=4997.3,5002.8
Exp/Cntr=0.3,0.1

Type RM Length L Ch R = 1,12696,283,283,283
BEGIN DESCRIPTION:
Elm 01 17 14.0
END DESCRIPTION:
XS GIS Cut Line= 3
      1563943.49      6823944.00      1564672.35      6823056.41
      1565168.66      6822088.89
#Sta/Elev= 30
  3851.5 1808.13  3863.7 1808.22  3898.9 1805.37  3927.6 1805.91  4041.0 1805.07
  4162.3 1805.71  4483.3 1803.69  4617.2 1803.47  4787.6 1800.67  4868.9 1800.24
  4950.8 1797.12  4997.3 1796.08  4997.7 1795.58  5002.3 1795.58  5002.8 1796.08
  5104.7 1797.45  5178.0 1801.31  5232.2 1802.75  5371.0 1804.63  5409.8 1804.26
  5482.0 1805.78  5548.9 1806.21  5587.3 1806.68  5626.1 1808.13  5661.3 1807.09
  5768.5 1807.30  5783.2 1807.34  5818.7 1807.80  5983.1 1807.63  6087.4 1807.85
#Mann=10,-1,0
  3851.5    0.07       0  4483.3   0.045       0  4787.6    0.07       0
  4868.9   0.045       0  4997.3   0.045       0  5002.8   0.045       0
  5548.9    0.07       0  5768.5    0.16       0  5783.2    0.07       0
  5983.1    0.16       0
Bank Sta=4997.3,5002.8
Exp/Cntr=0.3,0.1

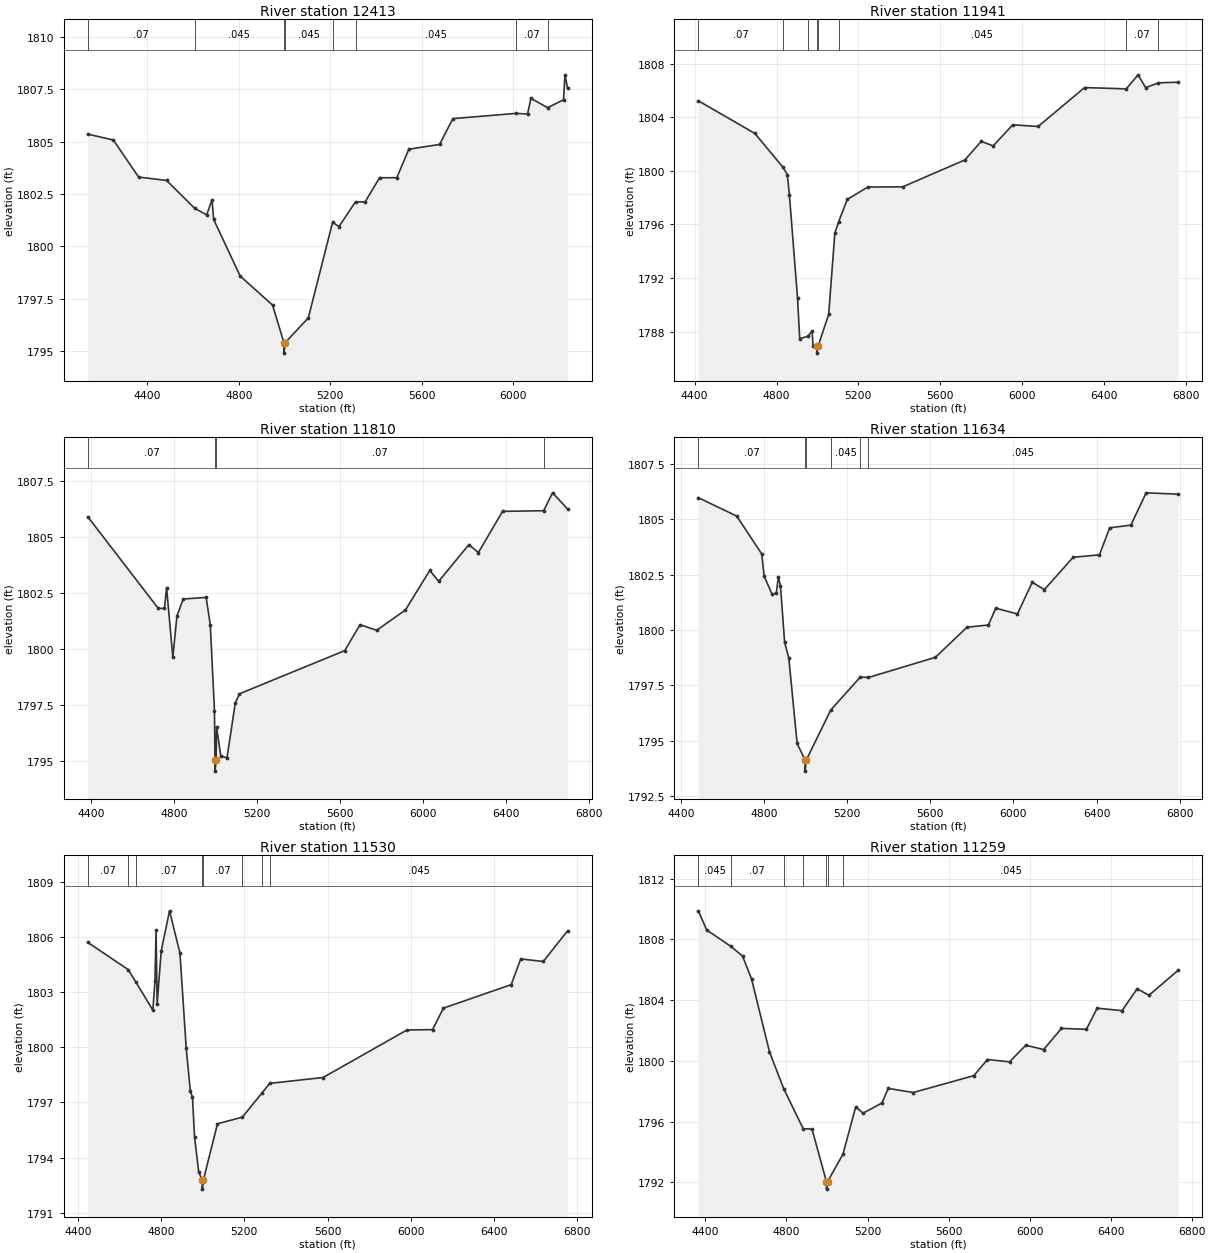
Type RM Length L Ch R = 1,12413,472,472,472
BEGIN DESCRIPTION:
Elm 01 17 13.6
END DESCRIPTION:
XS GIS Cut Line= 4
      1564139.75      6823738.04      1564710.44      6823393.71
      1565226.71      6822943.54      1565689.71      6822357.32
#Sta/Elev= 30
  4139.5 1805.36  4251.3 1805.08  4361.9 1803.31  4484.3 1803.15  4607.0 1801.82
  4659.5 1801.51  4682.9 1802.23  4690.0 1801.29  4805.8 1798.59  4947.7 1797.20
  4997.3 1795.41  4997.7 1794.91  5002.8 1795.41  5104.0 1796.59  5210.1 1801.15
  5238.2 1800.95  5310.4 1802.13  5352.1 1802.12  5415.7 1803.28  5491.0 1803.28
  5543.7 1804.64  5678.3 1804.87  5736.1 1806.10  6012.5 1806.35  6063.1 1806.32
  6077.5 1807.07  6150.8 1806.62  6220.2 1807.00  6226.5 1808.19  6238.0 1807.54
#Mann=8,-1,0
  4139.5    0.07       0  4607.0   0.045       0  4997.3   0.045       0
  5002.8   0.045       0  5210.1    0.07       0  5310.4   0.045       0
  6012.5    0.07       0  6150.8    0.16       0
Bank Sta=4997.3,5002.8
Exp/Cntr=0.3,0.1

Type RM Length L Ch R = 1,11941,131,131,131
BEGIN DESCRIPTION:
Elm 01 17 13.44
END DESCRIPTION:
XS GIS Cut Line= 3
      1564214.41      6823721.35      1565047.34      6823603.82
      1565812.18      6822308.45
#Sta/Elev= 30
  4418.0 1805.24  4694.4 1802.80  4830.1 1800.30  4852.9 1799.73  4863.0 1798.21
  4902.8 1790.51  4913.5 1787.47  4953.1 1787.65  4973.9 1788.04  4978.9 1786.89
  4997.2 1786.89  4997.7 1786.39  5002.8 1786.89  5055.1 1789.29  5085.1 1795.35
  5103.4 1796.19  5145.7 1797.87  5246.7 1798.80  5416.4 1798.81  5720.7 1800.82
  5800.7 1802.21  5859.2 1801.87  5954.9 1803.45  6078.9 1803.32  6306.1 1806.23
  6509.3 1806.13  6567.5 1807.18  6604.6 1806.22  6666.9 1806.58  6763.5 1806.63
#Mann=8,-1,0
  4418.0    0.07       0  4830.1   0.045       0  4953.1    0.07       0
  4997.2    0.07       0  5002.8    0.07       0  5103.4   0.045       0
  6509.3    0.07       0  6666.9    0.16       0
Bank Sta=4997.2,5002.8
Exp/Cntr=0.3,0.1

Type RM Length L Ch R = 1,11810,176,176,176
BEGIN DESCRIPTION:
Elm 01 17 13.42
END DESCRIPTION:
XS GIS Cut Line= 3
      1564236.59      6823784.10      1565040.81      6823723.66
      1565805.60      6822428.38
#Sta/Elev= 30
  4384.7 1805.91  4724.1 1801.81  4754.1 1801.81  4764.2 1802.74  4794.3 1799.63
  4814.3 1801.48  4844.4 1802.23  4954.7 1802.30  4974.8 1801.07  4994.8 1797.22
  4997.2 1795.03  4997.7 1794.53  5002.9 1795.03  5004.8 1796.52  5024.9 1795.22
  5055.0 1795.12  5095.1 1797.58  5115.2 1797.99  5622.0 1799.92  5696.1 1801.08
  5776.1 1800.83  5914.6 1801.74  6031.7 1803.51  6074.6 1803.02  6219.7 1804.66
  6265.9 1804.31  6382.3 1806.15  6580.2 1806.18  6622.9 1806.98  6695.4 1806.26
#Mann=4,-1,0
  4384.7    0.07       0  4997.2    0.07       0  5002.9    0.07       0
  6580.2    0.07       0
Bank Sta=4997.2,5002.9
Exp/Cntr=0.3,0.1

Type RM Length L Ch R = 1,11634,104,104,104
BEGIN DESCRIPTION:
Elm 01 17 13.41
END DESCRIPTION:
XS GIS Cut Line= 3
      1564240.90      6823916.41      1565045.13      6823855.97
      1565809.25      6822561.82
#Sta/Elev= 30
  4483.6 1805.97  4668.2 1805.14  4788.6 1803.43  4799.8 1802.44  4838.7 1801.60
  4858.8 1801.67  4868.8 1802.39  4878.8 1801.99  4898.9 1799.43  4918.9 1798.73
  4959.0 1794.87  4997.2 1794.12  4997.7 1793.62  5002.9 1794.12  5120.8 1796.38
  5263.1 1797.87  5302.3 1797.85  5624.5 1798.76  5776.5 1800.12  5880.0 1800.22
  5915.0 1800.98  6019.4 1800.72  6090.6 1802.15  6149.2 1801.82  6287.7 1803.28
  6414.2 1803.39  6463.3 1804.61  6565.2 1804.73  6638.9 1806.19  6793.0 1806.13
#Mann=6,-1,0
  4483.6    0.07       0  4997.2    0.07       0  5002.9    0.07       0
  5120.8   0.045       0  5263.1    0.07       0  5302.3   0.045       0
Bank Sta=4997.2,5002.9
Exp/Cntr=0.3,0.1

Type RM Length L Ch R = 1,11530,271,271,271
BEGIN DESCRIPTION:
Elm 01 17 13.4
END DESCRIPTION:
XS GIS Cut Line= 3
      1564252.80      6824007.66      1565056.96      6823947.22
      1565820.56      6822653.95
#Sta/Elev= 30
  4446.7 1805.72  4640.9 1804.24  4678.0 1803.56  4759.8 1802.03  4769.8 1803.61
  4775.3 1806.37  4780.3 1802.35  4799.9 1805.25  4840.0 1807.44  4890.1 1805.14
  4920.2 1799.96  4940.3 1797.60  4950.3 1797.30  4960.3 1795.13  4980.4 1793.21
  4997.2 1792.78  4997.7 1792.28  5002.9 1792.78  5070.7 1795.84  5190.1 1796.20
  5283.6 1797.50  5321.9 1798.04  5578.5 1798.36  5982.4 1800.95  6105.3 1800.97
  6158.0 1802.14  6483.8 1803.42  6529.6 1804.82  6637.9 1804.68  6755.0 1806.35
#Mann=8,-1,0
  4446.7    0.07       0  4640.9   0.045       0  4678.0    0.07       0
  4997.2    0.07       0  5002.9    0.07       0  5190.1   0.045       0
  5283.6    0.07       0  5321.9   0.045       0
Bank Sta=4997.2,5002.9
Exp/Cntr=0.3,0.1

Type RM Length L Ch R = 1,11259,433,433,433
BEGIN DESCRIPTION:
Elm 01 17 13.2
END DESCRIPTION:
XS GIS Cut Line= 3
      1564691.04      6824729.43      1565054.89      6824026.75
      1565850.11      6822664.69
#Sta/Elev= 30
  4365.0 1809.88  4406.1 1808.62  4524.2 1807.55  4583.2 1806.90  4627.5 1805.40
  4716.0 1800.60  4786.6 1798.16  4882.4 1795.54  4926.1 1795.51  4997.1 1792.06
  4997.6 1791.56  5002.9 1792.06  5078.8 1793.86  5141.8 1796.98  5178.0 1796.56
  5271.0 1797.23  5302.4 1798.19  5425.6 1797.92  5724.9 1799.03  5791.7 1800.09
  5901.0 1799.94  5981.2 1801.03  6069.6 1800.75  6157.3 1802.14  6280.5 1802.08
  6333.4 1803.47  6456.6 1803.31  6531.0 1804.75  6589.7 1804.32  6733.5 1805.97
#Mann=7,-1,0
  4365.0   0.045       0  4524.2    0.07       0  4786.6   0.045       0
  4882.4    0.07       0  4997.1    0.07       0  5002.9    0.07       0
  5078.8   0.045       0
Bank Sta=4997.1,5002.9
Exp/Cntr=0.3,0.1