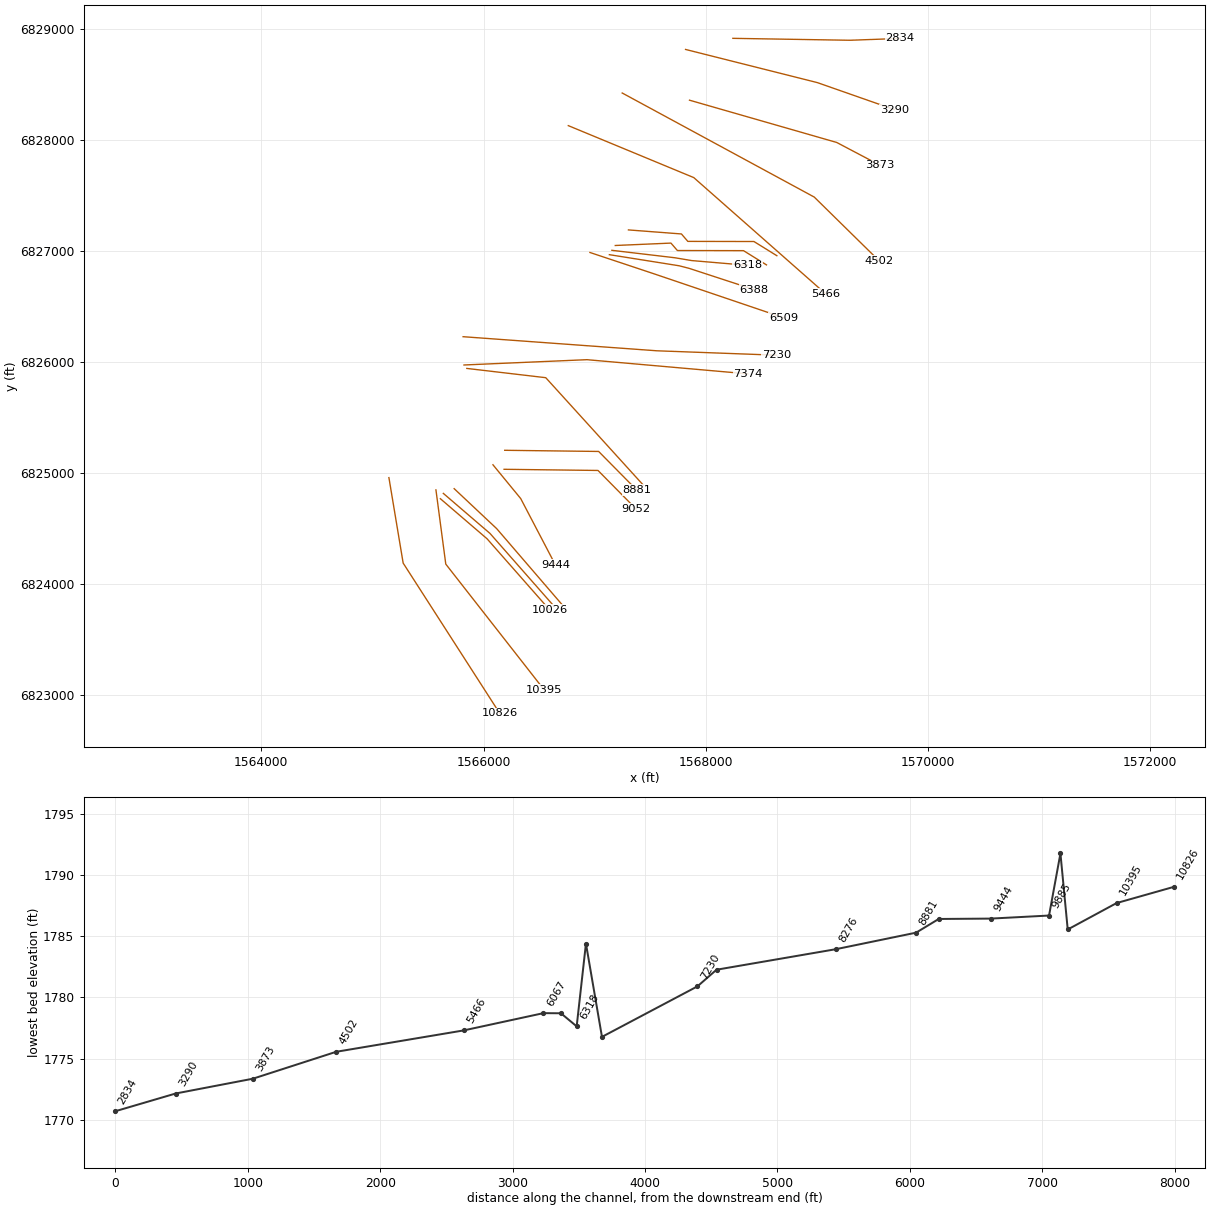
HEC-RAS study Elm 01 17.prj: Elm 01 17 Base Level Engineering

--- Elm 01 17.g01 (geometry) --- (continued)

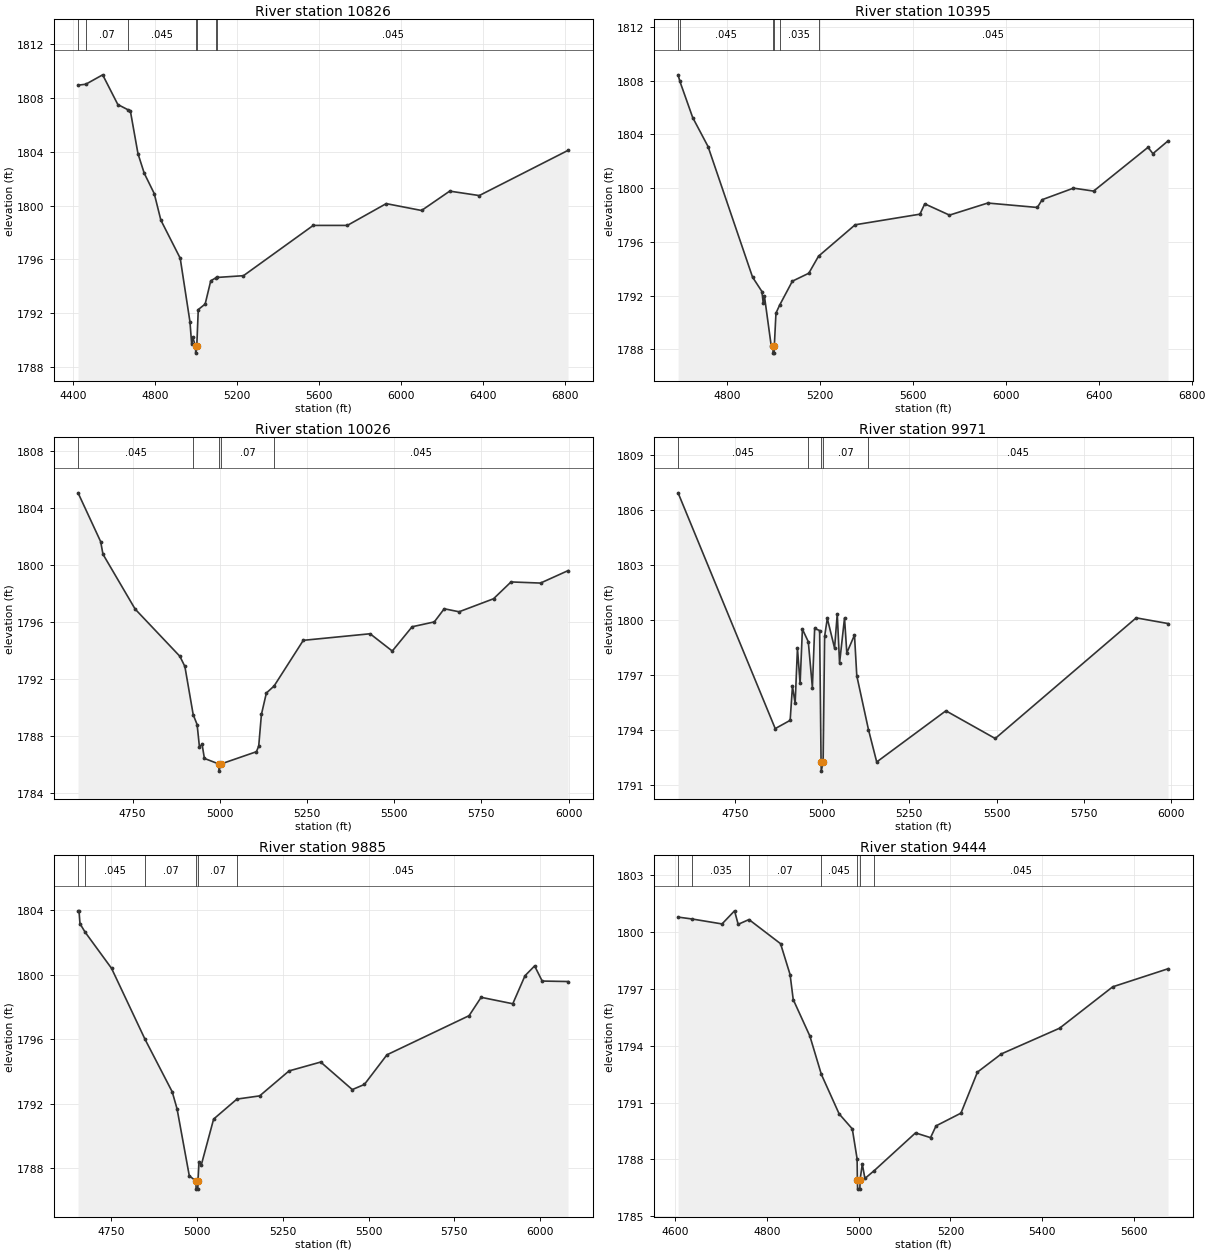
Type RM Length L Ch R = 1,10826,431,431,431
BEGIN DESCRIPTION:
Elm 01 17 13.0
END DESCRIPTION:
XS GIS Cut Line= 3
      1565148.43      6824956.47      1565276.71      6824186.46
      1566146.37      6822832.53
#Sta/Elev= 30
  4423.8 1808.96  4461.5 1809.03  4543.9 1809.73  4617.9 1807.52  4668.8 1807.12
  4678.8 1807.06  4716.2 1803.86  4746.7 1802.41  4795.4 1800.90  4827.8 1798.92
  4922.1 1796.09  4969.7 1791.36  4977.9 1789.72  4983.0 1790.21  4997.1 1789.53
  4997.6 1789.03  5002.9 1789.53  5010.2 1792.27  5043.8 1792.68  5071.1 1794.41
  5098.2 1794.65  5102.7 1794.66  5230.7 1794.79  5571.0 1798.53  5737.4 1798.53
  5926.9 1800.15  6099.3 1799.64  6236.6 1801.08  6380.7 1800.75  6813.6 1804.11
#Mann=7,-1,0
  4423.8   0.045       0  4461.5    0.07       0  4668.8   0.045       0
  4997.1   0.045       0  5002.9   0.045       0  5098.2   0.035       0
  5102.7   0.045       0
Bank Sta=4997.1,5002.9
Exp/Cntr=0.3,0.1

Type RM Length L Ch R = 1,10395,369,369,369
BEGIN DESCRIPTION:
Elm 01 17 12.0
END DESCRIPTION:
XS GIS Cut Line= 3
      1565571.80      6824845.88      1565660.38      6824177.30
      1566544.33      6823046.64
#Sta/Elev= 30
  4588.7 1808.44  4596.6 1807.95  4651.6 1805.26  4717.7 1803.10  4909.4 1793.37
  4949.7 1792.30  4955.2 1791.45  4960.3 1791.99  4990.1 1788.21  4997.1 1788.21
  4997.6 1787.71  5002.5 1787.71  5003.0 1788.21  5010.2 1790.69  5025.6 1791.27
  5080.8 1793.07  5151.5 1793.66  5193.4 1794.93  5351.1 1797.27  5630.0 1798.06
  5650.8 1798.83  5757.3 1797.99  5922.1 1798.89  6135.5 1798.56  6156.3 1799.14
  6291.1 1800.00  6377.8 1799.78  6612.1 1803.04  6633.1 1802.57  6698.3 1803.52
#Mann=6,-1,0
  4588.7   0.035       0  4596.6   0.045       0  4997.1   0.045       0
  5003.0   0.045       0  5025.6   0.035       0  5193.4   0.045       0
Bank Sta=4997.1,5003
Exp/Cntr=0.3,0.1

Type RM Length L Ch R = 1,10026,55,55,55
BEGIN DESCRIPTION:
Elm 01 17 11.4
END DESCRIPTION:
XS GIS Cut Line= 3
      1565611.84      6824766.27      1566032.09      6824405.41
      1566594.24      6823766.14
#Sta/Elev= 30
  4593.3 1805.04  4658.2 1801.62  4664.8 1800.74  4757.0 1796.90  4885.4 1793.59
  4899.7 1792.88  4923.6 1789.50  4934.8 1788.81  4941.4 1787.26  4949.1 1787.42
  4955.7 1786.44  4997.1 1786.05  4997.6 1785.55  5003.0 1786.05  5104.9 1786.91
  5111.5 1787.31  5119.2 1789.52  5133.4 1791.02  5155.5 1791.51  5239.3 1794.71
  5430.9 1795.17  5494.5 1793.96  5551.4 1795.66  5615.0 1796.00  5643.5 1796.92
  5686.1 1796.71  5784.8 1797.62  5835.1 1798.80  5919.6 1798.72  5998.5 1799.59
#Mann=5,-1,0
  4593.3   0.045       0  4923.6    0.07       0  4997.1    0.07       0
  5003.0    0.07       0  5155.5   0.045       0
Bank Sta=4997.1,5003
Exp/Cntr=0.3,0.1

Type RM Length L Ch R = 1,9971,86,86,86
BEGIN DESCRIPTION:
Elm 01 17 11.2
END DESCRIPTION:
XS GIS Cut Line= 3
      1565638.49      6824814.26      1566058.76      6824453.38
      1566620.43      6823814.66
#Sta/Elev= 30
  4587.2 1806.95  4865.7 1794.09  4908.5 1794.54  4915.1 1796.40  4922.8 1795.47
  4929.4 1798.47  4937.0 1796.55  4943.6 1799.51  4960.5 1798.83  4972.2 1796.33
  4978.7 1799.55  4993.0 1799.44  4997.1 1792.27  4997.6 1791.77  5003.0 1792.27
  5007.3 1799.12  5015.0 1800.10  5035.8 1798.48  5043.5 1800.35  5050.1 1797.66
  5064.3 1800.12  5070.9 1798.22  5092.9 1799.19  5099.5 1796.97  5132.9 1794.04
  5156.6 1792.27  5354.9 1795.06  5496.3 1793.55  5900.4 1800.13  5991.7 1799.82
#Mann=5,-1,0
  4587.2   0.045       0  4960.5    0.07       0  4997.1    0.07       0
  5003.0    0.07       0  5132.9   0.045       0
Bank Sta=4997.1,5003
Exp/Cntr=0.3,0.1

Type RM Length L Ch R = 1,9885,441,441,441
BEGIN DESCRIPTION:
Elm 01 17 11.0
END DESCRIPTION:
XS GIS Cut Line= 3
      1565735.89      6824856.97      1566118.91      6824496.54
      1566706.63      6823813.01
#Sta/Elev= 30
  4653.6 1803.97  4656.4 1803.97  4659.3 1803.17  4674.1 1802.65  4751.2 1800.40
  4848.6 1796.00  4928.0 1792.73  4942.1 1791.67  4977.7 1787.52  4997.1 1787.19
  4997.6 1786.69  5002.5 1786.69  5003.0 1787.19  5006.1 1788.40  5012.9 1788.21
  5048.6 1791.04  5116.4 1792.28  5182.7 1792.48  5268.3 1794.03  5360.5 1794.58
  5452.6 1792.87  5487.8 1793.19  5553.5 1795.03  5792.8 1797.46  5827.9 1798.60
  5920.1 1798.20  5955.7 1799.94  5983.7 1800.55  6005.7 1799.61  6081.0 1799.58
#Mann=6,-1,0
  4653.6   0.035       0  4674.1   0.045       0  4848.6    0.07       0
  4997.1    0.07       0  5003.0    0.07       0  5116.4   0.045       0
Bank Sta=4997.1,5003
Exp/Cntr=0.3,0.1

Type RM Length L Ch R = 1,9444,392,392,392
BEGIN DESCRIPTION:
Elm 01 17 10.0
END DESCRIPTION:
XS GIS Cut Line= 3
      1566085.09      6825072.16      1566335.13      6824767.54
      1566647.66      6824169.48
#Sta/Elev= 30
  4605.9 1800.76  4636.6 1800.66  4701.8 1800.40  4729.1 1801.09  4737.0 1800.38
  4760.6 1800.63  4829.5 1799.36  4850.3 1797.73  4857.1 1796.42  4893.4 1794.50
  4918.5 1792.48  4957.3 1790.40  4986.0 1789.61  4996.5 1788.03  4997.1 1786.94
  4997.6 1786.44  5002.5 1786.44  5003.0 1786.94  5007.8 1787.76  5013.5 1787.00
  5034.1 1787.42  5123.9 1789.40  5156.7 1789.15  5168.7 1789.77  5223.0 1790.44
  5259.0 1792.60  5311.3 1793.56  5438.1 1794.91  5554.1 1797.09  5674.8 1798.04
#Mann=7,-1,0
  4605.9    0.07       0  4636.6   0.035       0  4760.6    0.07       0
  4918.5   0.045       0  4997.1    0.07       0  5003.0   0.045       0
  5034.1   0.045       0
Bank Sta=4997.1,5003
Exp/Cntr=0.3,0.1

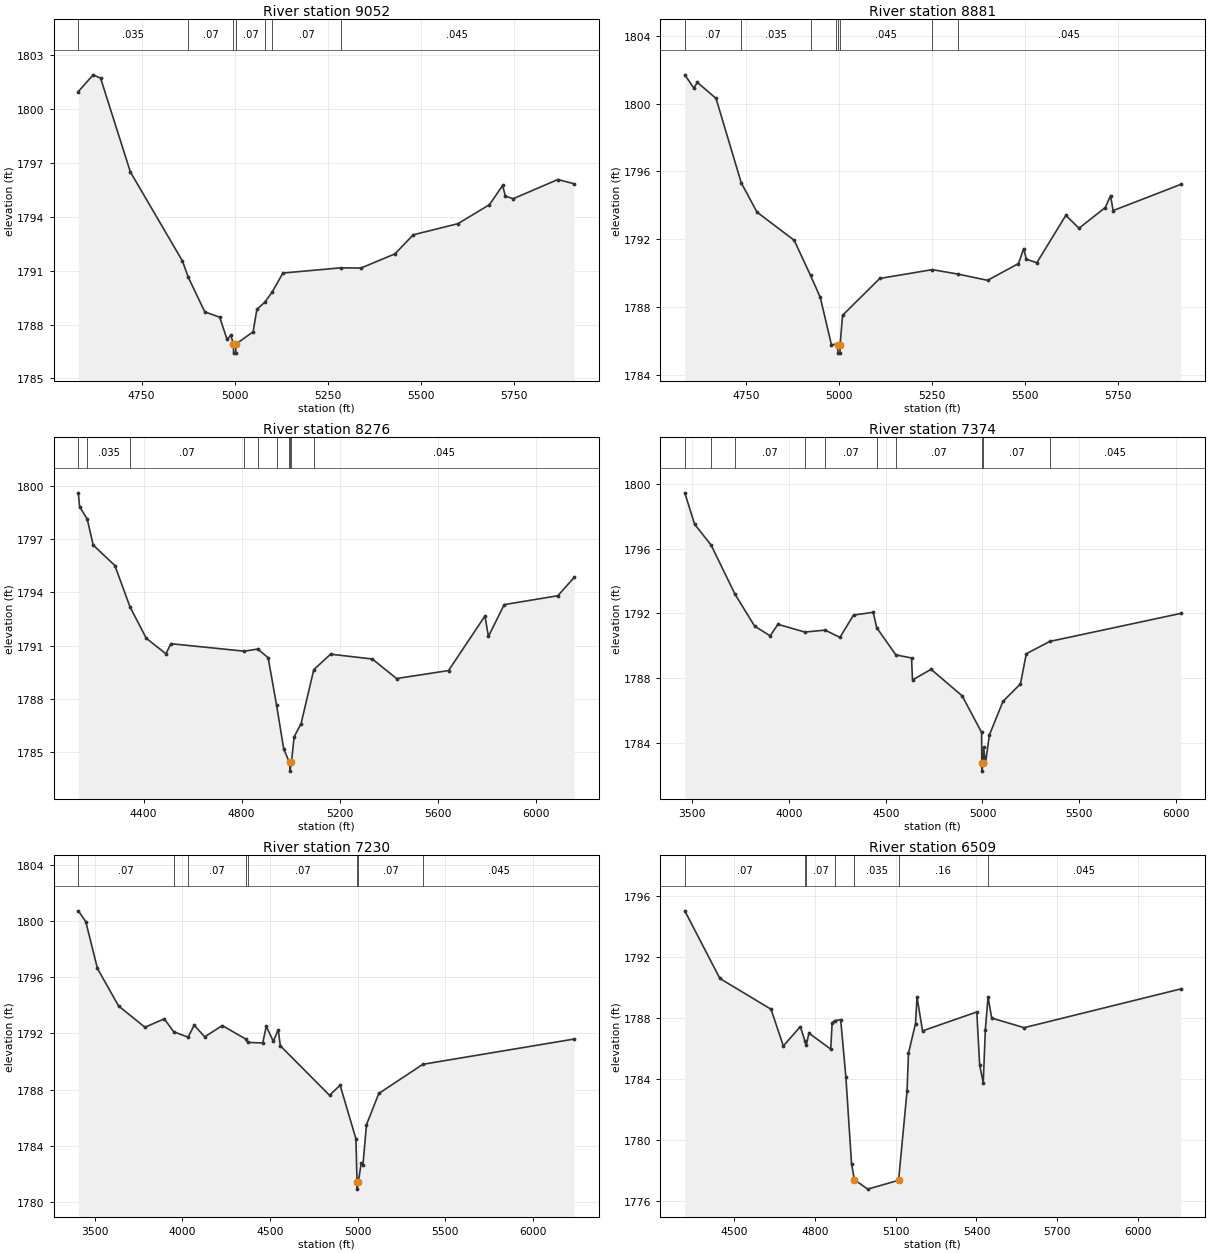
Type RM Length L Ch R = 1,9052,171,171,171
BEGIN DESCRIPTION:
Elm 01 17 9.2
END DESCRIPTION:
XS GIS Cut Line= 3
      1566185.13      6825031.42      1567030.82      6825020.94
      1567373.02      6824674.24
#Sta/Elev= 30
  4579.8 1800.98  4619.7 1801.91  4639.7 1801.72  4719.7 1796.50  4859.7 1791.54
  4874.9 1790.66  4919.7 1788.71  4959.7 1788.41  4979.7 1787.17  4989.7 1787.41
  4996.7 1786.91  4997.2 1786.41  5002.8 1786.41  5003.3 1786.91  5049.7 1787.60
  5059.7 1788.84  5081.2 1789.25  5100.9 1789.81  5129.7 1790.87  5284.9 1791.16
  5339.7 1791.15  5431.1 1791.94  5480.1 1793.00  5600.3 1793.62  5685.1 1794.68
  5720.5 1795.75  5727.6 1795.16  5748.8 1795.01  5869.0 1796.08  5912.7 1795.84
#Mann=7,-1,0
  4579.8   0.035       0  4874.9    0.07       0  4996.7    0.07       0
  5003.3    0.07       0  5081.2   0.045       0  5100.9    0.07       0
  5284.9   0.045       0
Bank Sta=4996.7,5003.3
Exp/Cntr=0.3,0.1

Type RM Length L Ch R = 1,8881,605,605,605
BEGIN DESCRIPTION:
Elm 01 17 9.0
END DESCRIPTION:
XS GIS Cut Line= 3
      1566190.97      6825202.60      1567036.67      6825192.12
      1567378.86      6824845.41
#Sta/Elev= 30
  4585.7 1801.69  4609.7 1800.92  4619.7 1801.24  4669.7 1800.30  4737.4 1795.33
  4779.7 1793.60  4879.8 1791.94  4923.7 1789.87  4949.8 1788.58  4979.8 1785.79
  4993.1 1785.81  4996.7 1785.79  4997.2 1785.29  5002.8 1785.29  5003.3 1785.79
  5009.8 1787.52  5109.8 1789.69  5251.1 1790.21  5319.6 1789.95  5399.8 1789.58
  5482.7 1790.57  5496.8 1791.45  5503.9 1790.82  5532.2 1790.62  5610.0 1793.41
  5645.4 1792.65  5716.1 1793.87  5730.2 1794.57  5737.2 1793.69  5918.6 1795.23
#Mann=8,-1,0
  4585.7    0.07       0  4737.4   0.035       0  4923.7    0.07       0
  4993.1   0.045       0  4996.7   0.045       0  5003.3   0.045       0
  5251.1    0.07       0  5319.6   0.045       0
Bank Sta=4996.7,5003.3
Exp/Cntr=0.3,0.1

Type RM Length L Ch R = 1,8276,902,902,902
BEGIN DESCRIPTION:
Elm 01 17 8.5
END DESCRIPTION:
XS GIS Cut Line= 3
      1565849.94      6825940.13      1566560.54      6825856.67
      1567439.05      6824888.54
#Sta/Elev= 30
  4134.0 1799.60  4139.1 1798.82  4170.1 1798.13  4194.8 1796.66  4283.0 1795.51
  4344.9 1793.18  4411.0 1791.42  4491.5 1790.54  4511.6 1791.11  4810.8 1790.69
  4865.9 1790.81  4908.3 1790.32  4942.6 1787.67  4971.9 1785.19  4994.9 1784.44
  4996.6 1784.44  4997.1 1783.94  5003.4 1784.44  5014.4 1785.87  5042.8 1786.62
  5094.6 1789.65  5163.1 1790.52  5333.4 1790.25  5432.1 1789.15  5644.4 1789.60
  5792.9 1792.67  5807.1 1791.52  5871.3 1793.31  6090.3 1793.81  6156.8 1794.84
#Mann=10,-1,0
  4134.0    0.07       0  4170.1   0.035       0  4344.9    0.07       0
  4810.8   0.035       0  4865.9    0.07       0  4942.6   0.035       0
  4994.9    0.07       0  4996.6    0.07       0  5003.4    0.07       0
  5094.6   0.045       0
Bank Sta=4996.6,5003.4
Exp/Cntr=0.3,0.1

Type RM Length L Ch R = 1,7374,144,144,144
BEGIN DESCRIPTION:
Elm 01 17 8.0
END DESCRIPTION:
XS GIS Cut Line= 3
      1565824.24      6825971.19      1566931.40      6826018.93
      1568379.19      6825891.26
#Sta/Elev= 30
  3462.1 1799.45  3512.9 1797.51  3598.2 1796.22  3721.9 1793.18  3823.2 1791.21
  3903.3 1790.62  3943.3 1791.33  4082.3 1790.85  4187.1 1790.97  4263.6 1790.52
  4333.7 1791.90  4435.7 1792.07  4453.5 1791.12  4552.5 1789.44  4633.5 1789.25
  4638.5 1787.89  4734.5 1788.55  4895.1 1786.91  4995.5 1784.65  4996.4 1782.76
  4996.9 1782.26  5003.7 1782.76  5005.6 1783.75  5015.6 1782.76  5035.7 1784.49
  5106.0 1786.57  5196.3 1787.65  5226.4 1789.51  5347.4 1790.27  6023.7 1792.00
#Mann=10,-1,0
  3462.1    0.07       0  3598.2   0.035       0  3721.9    0.07       0
  4082.3   0.035       0  4187.1    0.07       0  4453.5   0.045       0
  4552.5    0.07       0  4996.4    0.07       0  5003.7    0.07       0
  5347.4   0.045       0
Bank Sta=4996.4,5003.7
Exp/Cntr=0.3,0.1

Type RM Length L Ch R = 1,7230,721,721,721
BEGIN DESCRIPTION:
Elm 01 17 7.0
END DESCRIPTION:
XS GIS Cut Line= 3
      1565816.24      6826225.96      1567562.06      6826098.95
      1568638.29      6826059.31
#Sta/Elev= 30
  3407.0 1800.74  3449.4 1799.97  3516.0 1796.63  3636.4 1793.96  3786.8 1792.44
  3897.1 1793.04  3950.7 1792.12  4033.2 1791.73  4067.5 1792.59  4127.7 1791.76
  4227.9 1792.56  4361.6 1791.60  4372.9 1791.36  4458.5 1791.32  4478.6 1792.51
  4518.7 1791.44  4547.0 1792.26  4558.8 1791.12  4839.5 1787.59  4899.7 1788.31
  4989.9 1784.49  4996.3 1781.40  4996.8 1780.90  5003.7 1781.40  5020.0 1782.76
  5030.0 1782.63  5050.1 1785.49  5120.3 1787.72  5371.8 1789.80  6234.4 1791.60
#Mann=8,-1,0
  3407.0    0.07       0  3950.7   0.035       0  4033.2    0.07       0
  4361.6   0.045       0  4372.9    0.07       0  4996.3    0.07       0
  5003.7    0.07       0  5371.8   0.045       0
Bank Sta=4996.3,5003.7
Exp/Cntr=0.3,0.1

Type RM Length L Ch R = 1,6509,121,121,121
BEGIN DESCRIPTION:
Elm 01 17 6.0
END DESCRIPTION:
XS GIS Cut Line= 3
      1566958.23      6826984.63      1567533.38      6826793.08
      1568701.02      6826397.00
#Sta/Elev= 30
  4318.0 1795.04  4448.0 1790.60  4637.8 1788.58  4683.5 1786.17  4746.7 1787.44
  4763.9 1786.47  4768.3 1786.21  4778.4 1787.01  4859.3 1785.96  4864.6 1787.69
  4873.6 1787.83  4896.2 1787.89  4915.4 1784.16  4936.5 1778.44  4947.0 1777.39
  4996.6 1776.77  5111.0 1777.35  5142.4 1783.21  5147.7 1785.69  5173.8 1787.64
  5179.4 1789.38  5199.9 1787.16  5401.1 1788.40  5411.7 1784.94  5425.0 1783.74
  5432.8 1787.23  5442.8 1789.39  5456.4 1788.00  5576.8 1787.37  6157.2 1789.91
#Mann=7,-1,0
  4318.0    0.07       0  4763.9   0.035       0  4768.3    0.07       0
  4873.6   0.035       0  4947.0   0.035       0  5111.0    0.16       0
  5442.8   0.045       0
Bank Sta=4947,5111
Exp/Cntr=0.3,0.1

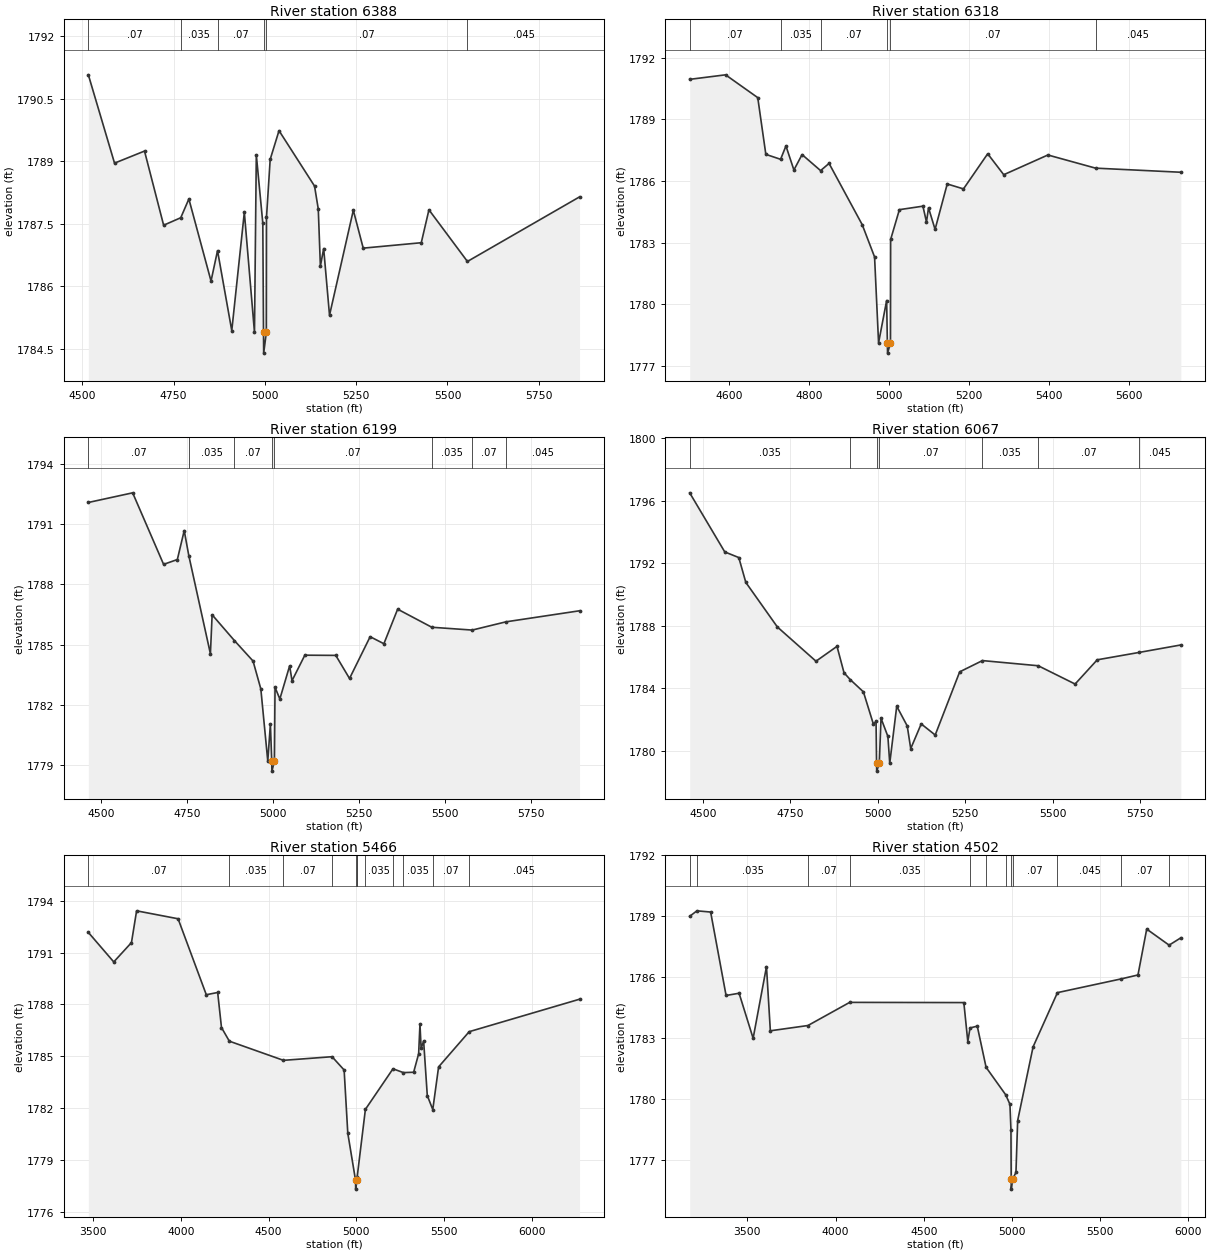
Type RM Length L Ch R = 1,6388,70,70,70
BEGIN DESCRIPTION:
Elm 01 17 5.5
END DESCRIPTION:
XS GIS Cut Line= 4
      1567133.15      6826964.88      1567761.54      6826864.90
      1567850.67      6826841.85      1568436.98      6826650.18
#Sta/Elev= 30
  4516.4 1791.08  4588.1 1788.96  4670.2 1789.25  4722.6 1787.47  4769.5 1787.65
  4791.7 1788.10  4852.4 1786.13  4870.2 1786.86  4909.2 1784.94  4943.6 1787.78
  4971.4 1784.90  4976.4 1789.16  4994.2 1787.52  4996.1 1784.90  4996.6 1784.40
  5003.9 1784.90  5004.3 1787.66  5014.4 1789.05  5038.6 1789.74  5135.9 1788.41
  5146.1 1787.86  5151.9 1786.49  5160.9 1786.91  5176.9 1785.31  5242.1 1787.83
  5269.2 1786.92  5428.2 1787.05  5449.2 1787.84  5554.6 1786.60  5861.6 1788.15
#Mann=6,-1,0
  4516.4    0.07       0  4769.5   0.035       0  4870.2    0.07       0
  4996.1    0.07       0  5003.9    0.07       0  5554.6   0.045       0
Bank Sta=4996.1,5003.9
Exp/Cntr=0.3,0.1

Type RM Length L Ch R = 1,6318,119,119,119
BEGIN DESCRIPTION:
Elm 01 17 5.3
END DESCRIPTION:
XS GIS Cut Line= 4
      1567155.94      6827004.13      1567723.26      6826937.10
      1567873.89      6826911.82      1568376.27      6826869.04
#Sta/Elev= 30
  4501.8 1790.95  4591.5 1791.17  4672.0 1790.06  4692.2 1787.30  4729.1 1787.06
  4742.5 1787.71  4762.4 1786.54  4782.8 1787.29  4829.1 1786.51  4850.3 1786.86
  4933.2 1783.88  4964.1 1782.31  4974.1 1778.13  4994.3 1780.19  4996.1 1778.13
  4996.6 1777.63  5003.9 1778.13  5004.3 1783.16  5026.2 1784.61  5085.0 1784.78
  5093.9 1784.01  5099.0 1784.70  5115.4 1783.65  5145.8 1785.86  5186.4 1785.62
  5247.0 1787.33  5287.1 1786.31  5397.5 1787.27  5516.7 1786.63  5730.0 1786.43
#Mann=6,-1,0
  4501.8    0.07       0  4729.1   0.035       0  4829.1    0.07       0
  4996.1    0.07       0  5003.9    0.07       0  5516.7   0.045       0
Bank Sta=4996.1,5003.9
Exp/Cntr=0.3,0.1

Type RM Length L Ch R = 1,6199,132,132,132
BEGIN DESCRIPTION:
Elm 01 17 5.1
END DESCRIPTION:
XS GIS Cut Line= 5
      1567186.32      6827047.66      1567687.64      6827069.27
      1567745.51      6827002.33      1568340.65      6827001.21
      1568547.57      6826872.88
#Sta/Elev= 30
  4462.6 1792.07  4591.5 1792.55  4681.5 1788.99  4721.5 1789.23  4741.5 1790.67
  4754.9 1789.42  4817.7 1784.54  4822.7 1786.48  4887.4 1785.20  4941.7 1784.18
  4964.4 1782.79  4984.6 1779.20  4992.2 1781.05  4996.1 1779.20  4996.6 1778.70
  5003.9 1779.20  5005.7 1782.87  5019.7 1782.29  5048.2 1783.94  5055.1 1783.20
  5092.4 1784.47  5182.4 1784.46  5222.4 1783.31  5282.4 1785.39  5322.4 1785.04
  5362.4 1786.76  5461.8 1785.86  5579.3 1785.72  5677.5 1786.13  5891.5 1786.68
#Mann=8,-1,0
  4462.6    0.07       0  4754.9   0.035       0  4887.4    0.07       0
  4996.1    0.07       0  5003.9    0.07       0  5461.8   0.035       0
  5579.3    0.07       0  5677.5   0.045       0
Bank Sta=4996.1,5003.9
Exp/Cntr=0.3,0.1

Type RM Length L Ch R = 1,6067,601,601,601
BEGIN DESCRIPTION:
Elm 01 17 5.0
END DESCRIPTION:
XS GIS Cut Line= 5
      1567304.98      6827188.00      1567781.80      6827151.54
      1567839.67      6827084.60      1568434.81      6827083.48
      1568640.95      6826955.63
#Sta/Elev= 30
  4461.8 1796.51  4562.1 1792.73  4602.2 1792.37  4622.3 1790.78  4712.5 1787.93
  4822.9 1785.74  4883.0 1786.69  4903.1 1785.00  4920.6 1784.57  4958.5 1783.78
  4987.0 1781.72  4994.7 1781.89  4996.1 1779.21  4996.6 1778.71  5003.9 1779.21
  5008.9 1782.09  5028.5 1780.93  5033.8 1779.21  5053.8 1782.86  5083.8 1781.60
  5093.8 1780.15  5123.8 1781.73  5163.8 1781.02  5233.8 1785.06  5298.9 1785.78
  5458.4 1785.45  5563.8 1784.28  5627.1 1785.83  5746.4 1786.30  5866.2 1786.78
#Mann=7,-1,0
  4461.8   0.035       0  4920.6    0.07       0  4996.1    0.07       0
  5003.9    0.07       0  5298.9   0.035       0  5458.4    0.07       0
  5746.4   0.045       0
Bank Sta=4996.1,5003.9
Exp/Cntr=0.3,0.1

Type RM Length L Ch R = 1,5466,964,964,964
BEGIN DESCRIPTION:
Elm 01 17 4.6
END DESCRIPTION:
XS GIS Cut Line= 3
      1566763.56      6828127.44      1567892.88      6827659.42
      1569077.01      6826615.11
#Sta/Elev= 30
  3472.0 1792.17  3616.9 1790.46  3717.9 1791.58  3747.2 1793.42  3983.8 1792.96
  4144.7 1788.56  4209.6 1788.69  4231.3 1786.66  4276.1 1785.87  4584.7 1784.76
  4861.9 1784.97  4930.8 1784.20  4951.7 1780.54  4996.1 1777.80  4996.6 1777.30
  5003.9 1777.80  5005.5 1778.03  5052.1 1781.92  5209.4 1784.27  5268.6 1784.05
  5327.3 1784.07  5355.8 1785.14  5363.3 1786.85  5370.0 1785.45  5384.2 1785.88
  5405.1 1782.72  5436.4 1781.91  5469.6 1784.38  5644.1 1786.42  6273.3 1788.30
#Mann=12,-1,0
  3472.0    0.07       0  4276.1   0.035       0  4584.7    0.07       0
  4861.9   0.035       0  4996.1   0.035       0  5003.9   0.035       0
  5005.5    0.07       0  5052.1   0.035       0  5209.4    0.07       0
  5268.6   0.035       0  5436.4    0.07       0  5644.1   0.045       0
Bank Sta=4996.1,5003.9
Exp/Cntr=0.3,0.1

Type RM Length L Ch R = 1,4502,629,629,629
BEGIN DESCRIPTION:
Elm 01 17 4.3
END DESCRIPTION:
XS GIS Cut Line= 3
      1567248.80      6828421.39      1568977.64      6827483.88
      1569561.08      6826910.21
#Sta/Elev= 30
  3173.1 1788.99  3214.2 1789.26  3291.9 1789.20  3379.4 1785.09  3453.2 1785.20
  3532.8 1782.98  3608.5 1786.51  3630.4 1783.35  3843.6 1783.61  4080.2 1784.75
  4727.5 1784.74  4750.0 1782.82  4762.7 1783.49  4803.6 1783.58  4853.7 1781.55
  4964.7 1780.20  4988.9 1779.73  4994.7 1778.46  4996.0 1776.05  4996.5 1775.55
  5004.1 1776.05  5023.0 1776.37  5032.7 1778.93  5120.2 1782.56  5258.3 1785.23
  5621.4 1785.91  5714.8 1786.10  5764.4 1788.36  5891.3 1787.57  5958.0 1787.93
#Mann=12,-1,0
  3173.1    0.07       0  3214.2   0.035       0  3843.6    0.07       0
  4080.2   0.035       0  4762.7    0.07       0  4853.7   0.035       0
  4964.7    0.07       0  4996.0    0.07       0  5004.1    0.07       0
  5258.3   0.045       0  5621.4    0.07       0  5891.3   0.045       0
Bank Sta=4996,5004.1
Exp/Cntr=0.3,0.1

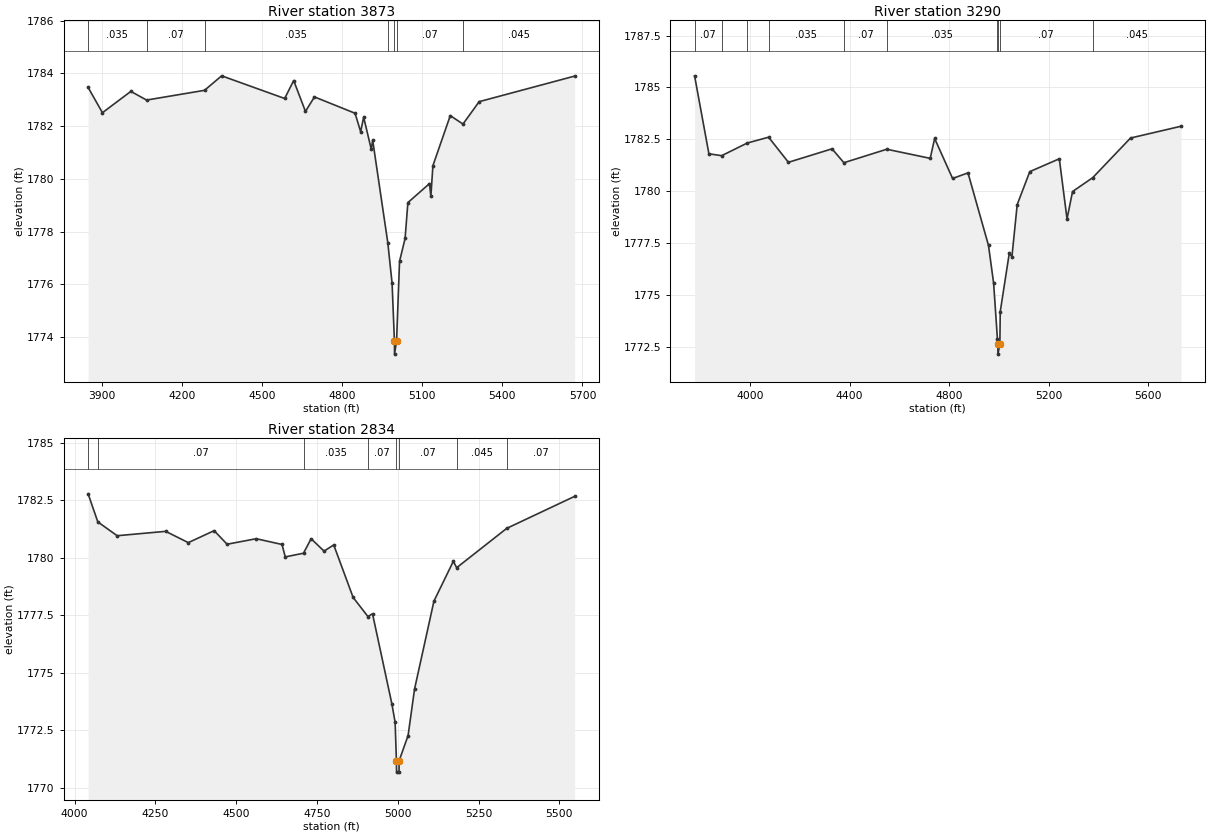
Type RM Length L Ch R = 1,3873,583,583,583
BEGIN DESCRIPTION:
Elm 01 17 4.0
END DESCRIPTION:
XS GIS Cut Line= 3
      1567854.52      6828356.68      1569179.81      6827975.89
      1569571.07      6827769.66
#Sta/Elev= 30
  3849.4 1783.47  3903.0 1782.51  4009.4 1783.32  4068.2 1782.99  4285.1 1783.36
  4349.3 1783.91  4585.2 1783.05  4618.9 1783.73  4663.0 1782.56  4696.7 1783.11
  4848.7 1782.49  4869.6 1781.79  4880.9 1782.34  4909.4 1781.12  4914.6 1781.47
  4971.2 1777.58  4987.3 1776.04  4996.0 1773.85  4996.5 1773.35  5004.1 1773.85
  5015.2 1776.87  5036.0 1777.74  5046.4 1779.10  5127.3 1779.82  5132.5 1779.34
  5140.1 1780.50  5205.1 1782.40  5252.6 1782.08  5313.3 1782.93  5670.6 1783.90
#Mann=7,-1,0
  3849.4   0.035       0  4068.2    0.07       0  4285.1   0.035       0
  4971.2    0.07       0  4996.0    0.07       0  5004.1    0.07       0
  5252.6   0.045       0
Bank Sta=4996,5004.1
Exp/Cntr=0.3,0.1

Type RM Length L Ch R = 1,3290,456,456,456
BEGIN DESCRIPTION:
Elm 01 17 3.0
END DESCRIPTION:
XS GIS Cut Line= 3
      1567819.12      6828813.80      1569005.39      6828515.10
      1569696.85      6828272.76
#Sta/Elev= 30
  3776.7 1785.56  3834.3 1781.80  3885.7 1781.71  3988.5 1782.32  4074.3 1782.60
  4154.0 1781.39  4329.3 1782.04  4377.0 1781.37  4549.4 1782.02  4724.1 1781.58
  4741.8 1782.54  4814.0 1780.61  4875.9 1780.88  4958.4 1777.38  4979.0 1775.56
  4994.3 1772.87  4995.9 1772.64  4996.4 1772.14  5004.1 1772.64  5005.6 1774.19
  5042.0 1777.01  5052.6 1776.84  5073.8 1779.35  5124.4 1780.94  5243.1 1781.56
  5274.1 1778.66  5296.3 1779.98  5377.5 1780.65  5529.4 1782.56  5732.7 1783.13
#Mann=10,-1,0
  3776.7    0.07       0  3885.7   0.045       0  3988.5    0.07       0
  4074.3   0.035       0  4377.0    0.07       0  4549.4   0.035       0
  4994.3    0.07       0  4995.9    0.07       0  5004.1    0.07       0
  5377.5   0.045       0
Bank Sta=4995.9,5004.1
Exp/Cntr=0.3,0.1

Type RM Length L Ch R = 1,2834,182,182,182
BEGIN DESCRIPTION:
Elm 01 17 2.9
END DESCRIPTION:
XS GIS Cut Line= 3
      1568245.08      6828913.91      1569299.19      6828896.53
      1569750.04      6828912.93
#Sta/Elev= 30
  4041.8 1782.78  4071.8 1781.56  4131.7 1780.96  4281.8 1781.15  4351.8 1780.66
  4431.8 1781.18  4471.8 1780.59  4561.8 1780.83  4641.8 1780.58  4651.8 1780.04
  4708.3 1780.20  4731.8 1780.83  4771.8 1780.29  4801.8 1780.56  4861.8 1778.28
  4907.6 1777.45  4921.8 1777.57  4981.8 1773.65  4991.8 1772.85  4995.8 1771.19
  4996.3 1770.69  5003.8 1770.69  5004.3 1771.19  5031.9 1772.28  5051.9 1774.30
  5111.9 1778.12  5171.9 1779.85  5182.2 1779.57  5337.1 1781.28  5547.2 1782.67
#Mann=8,-1,0
  4041.8   0.035       0  4071.8    0.07       0  4708.3   0.035       0
  4907.6    0.07       0  4995.8    0.07       0  5004.3    0.07       0
  5182.2   0.045       0  5337.1    0.07       0
Bank Sta=4995.8,5004.3
Exp/Cntr=0.3,0.1