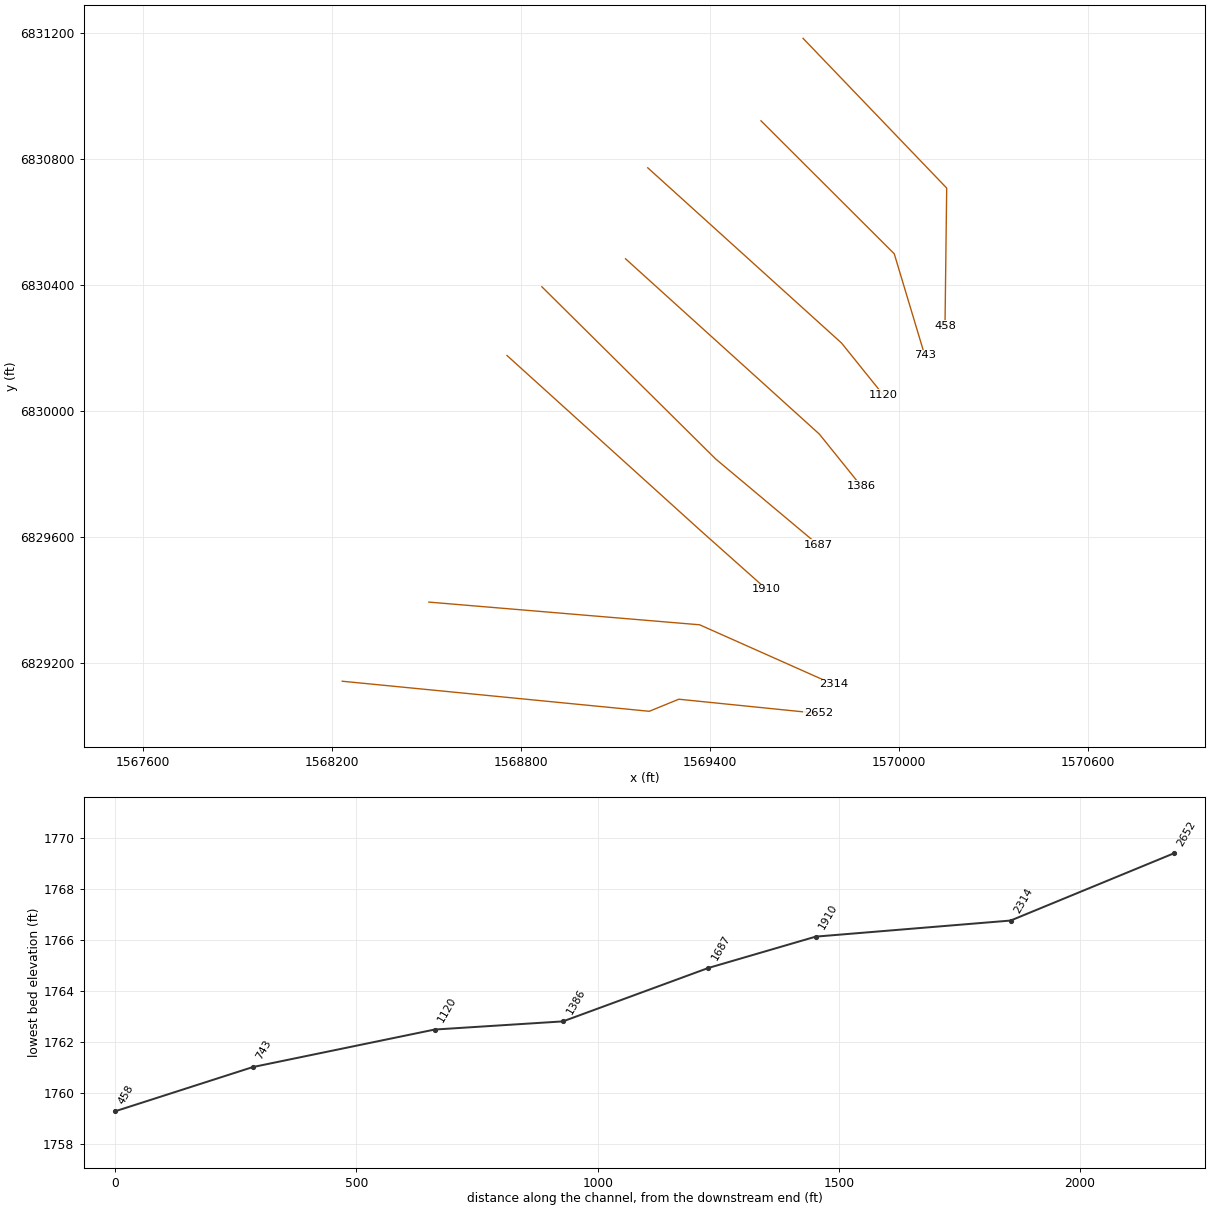
HEC-RAS study Elm 01 17.prj: Elm 01 17 Base Level Engineering

--- Elm 01 17.g01 (geometry) --- (continued)

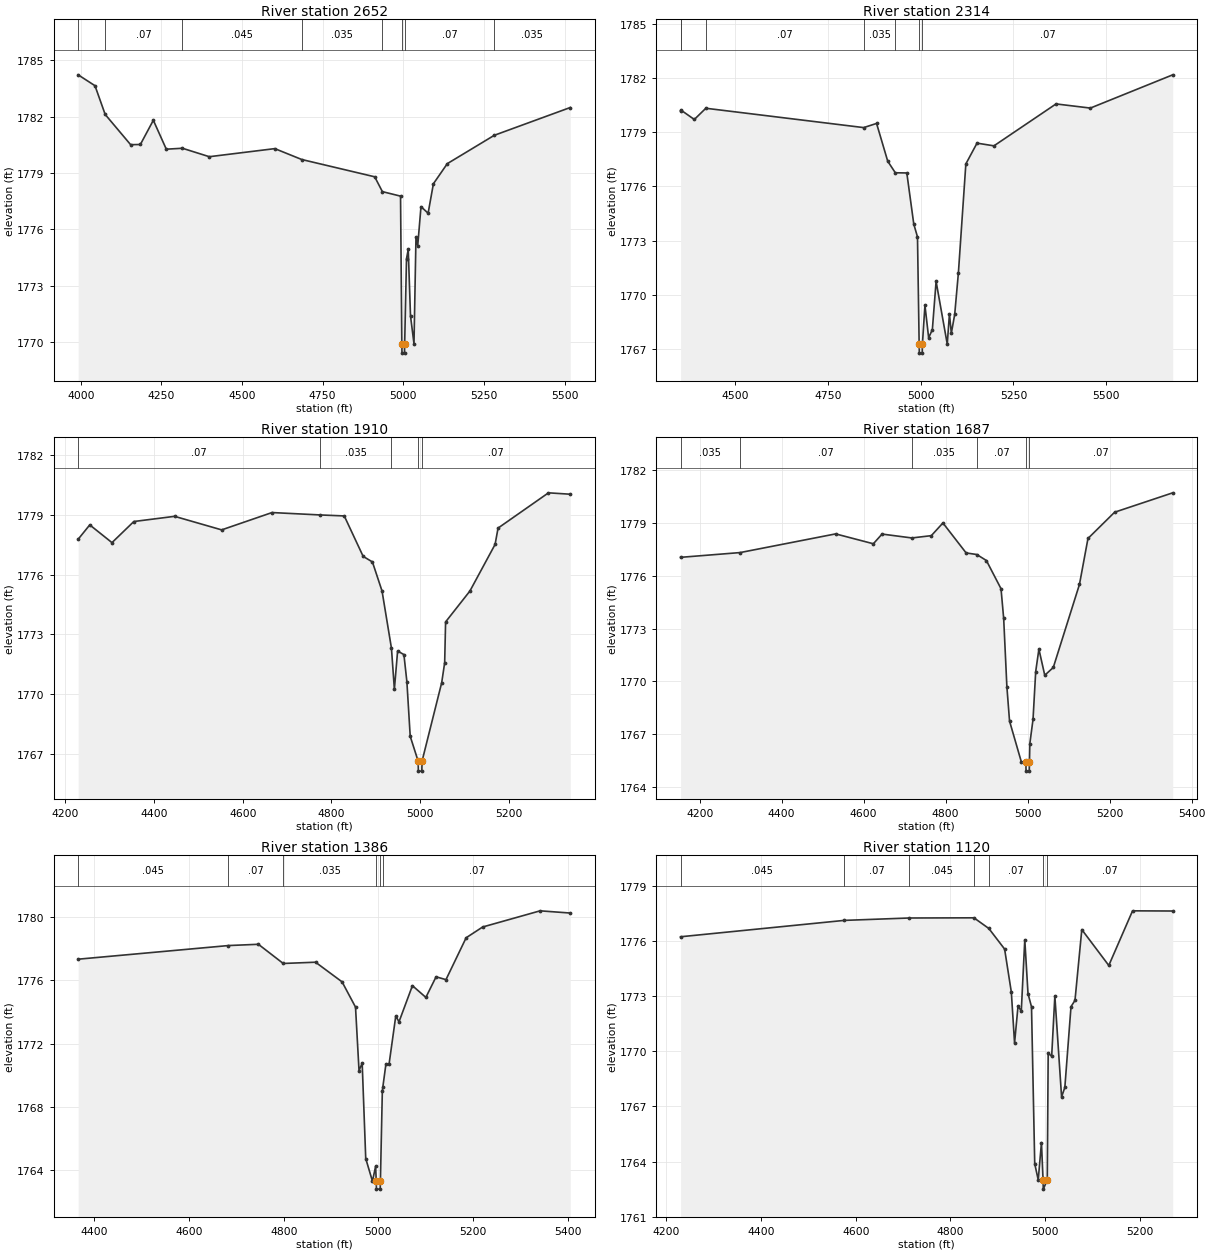
Type RM Length L Ch R = 1,2652,338,338,338
BEGIN DESCRIPTION:
Elm 01 17 2.8
END DESCRIPTION:
XS GIS Cut Line= 4
      1568233.03      6829142.39      1569207.91      6829046.95
      1569301.52      6829085.31      1569744.34      6829040.34
#Sta/Elev= 30
  3992.1 1784.22  4044.3 1783.64  4075.9 1782.11  4154.8 1780.50  4185.0 1780.51
  4225.2 1781.80  4265.4 1780.26  4315.4 1780.31  4398.7 1779.86  4601.8 1780.29
  4685.4 1779.71  4911.5 1778.79  4935.3 1778.00  4991.6 1777.76  4995.6 1769.90
  4996.1 1769.40  5003.9 1769.40  5004.4 1769.90  5010.1 1774.43  5015.5 1774.92
  5022.5 1771.38  5033.3 1769.90  5039.5 1775.59  5044.9 1775.13  5055.0 1777.20
  5077.1 1776.85  5093.5 1778.42  5136.6 1779.49  5282.3 1781.00  5517.9 1782.48
#Mann=8,-1,0
  3992.1   0.045       0  4075.9    0.07       0  4315.4   0.045       0
  4685.4   0.035       0  4935.3    0.07       0  4995.6    0.07       0
  5004.4    0.07       0  5282.3   0.035       0
Bank Sta=4995.6,5004.4
Exp/Cntr=0.3,0.1

Type RM Length L Ch R = 1,2314,404,404,404
BEGIN DESCRIPTION:
Elm 01 17 2.7
END DESCRIPTION:
XS GIS Cut Line= 3
      1568508.03      6829393.68      1569367.76      6829321.61
      1569792.63      6829132.49
#Sta/Elev= 30
  4351.9 1780.18  4352.8 1780.22  4389.0 1779.70  4420.1 1780.32  4845.9 1779.25
  4880.7 1779.48  4910.8 1777.39  4931.3 1776.75  4962.3 1776.74  4981.1 1773.91
  4991.1 1773.20  4995.6 1767.27  4996.1 1766.77  5003.9 1766.77  5004.4 1767.27
  5011.2 1769.42  5021.2 1767.62  5031.2 1768.07  5041.3 1770.74  5071.4 1767.27
  5077.3 1768.94  5082.4 1767.87  5091.5 1768.91  5101.5 1771.22  5121.6 1777.24
  5151.7 1778.39  5197.4 1778.24  5364.9 1780.56  5457.5 1780.33  5679.7 1782.17
#Mann=7,-1,0
  4351.9    0.07       0  4352.8   0.045       0  4420.1    0.07       0
  4845.9   0.035       0  4931.3    0.07       0  4995.6    0.07       0
  5004.4    0.07       0
Bank Sta=4995.6,5004.4
Exp/Cntr=0.3,0.1

Type RM Length L Ch R = 1,1910,223,223,223
BEGIN DESCRIPTION:
Elm 01 17 2.6
END DESCRIPTION:
XS GIS Cut Line= 3
      1568756.13      6830176.62      1569371.43      6829620.15
      1569580.70      6829433.84
#Sta/Elev= 30
  4228.9 1777.78  4255.1 1778.50  4305.2 1777.61  4354.5 1778.67  4446.4 1778.93
  4552.5 1778.25  4666.1 1779.12  4774.3 1779.00  4829.0 1778.95  4871.6 1776.92
  4892.5 1776.64  4914.2 1775.18  4935.4 1772.31  4942.0 1770.25  4949.3 1772.17
  4963.5 1771.99  4970.2 1770.63  4977.7 1767.89  4995.6 1766.64  4996.1 1766.14
  5003.9 1766.14  5004.4 1766.64  5048.7 1770.58  5055.4 1771.58  5057.5 1773.63
  5112.3 1775.18  5169.1 1777.52  5175.8 1778.34  5289.5 1780.11  5338.7 1780.04
#Mann=5,-1,0
  4228.9    0.07       0  4774.3   0.035       0  4935.4    0.07       0
  4995.6    0.07       0  5004.4    0.07       0
Bank Sta=4995.6,5004.4
Exp/Cntr=0.3,0.1

Type RM Length L Ch R = 1,1687,301,301,301
BEGIN DESCRIPTION:
Elm 01 17 2.4
END DESCRIPTION:
XS GIS Cut Line= 3
      1568866.86      6830394.81      1569418.94      6829847.90
      1569743.41      6829576.07
#Sta/Elev= 30
  4153.4 1777.04  4298.6 1777.31  4531.6 1778.37  4623.6 1777.81  4644.8 1778.36
  4717.5 1778.14  4765.0 1778.27  4793.3 1778.99  4849.9 1777.29  4875.9 1777.20
  4899.3 1776.86  4935.0 1775.26  4941.5 1773.57  4949.3 1769.70  4955.8 1767.75
  4984.5 1765.44  4995.6 1765.41  4996.1 1764.91  5003.9 1764.91  5004.4 1765.41
  5005.3 1766.47  5013.1 1767.85  5019.6 1770.56  5027.4 1771.83  5041.7 1770.35
  5062.5 1770.79  5126.3 1775.50  5147.1 1778.11  5212.1 1779.60  5353.8 1780.70
#Mann=6,-1,0
  4153.4   0.035       0  4298.6    0.07       0  4717.5   0.035       0
  4875.9    0.07       0  4995.6    0.07       0  5004.4    0.07       0
Bank Sta=4995.6,5004.4
Exp/Cntr=0.3,0.1

Type RM Length L Ch R = 1,1386,266,266,266
BEGIN DESCRIPTION:
Elm 01 17 2.3
END DESCRIPTION:
XS GIS Cut Line= 3
      1569132.44      6830483.75      1569747.75      6829927.28
      1569879.87      6829763.16
#Sta/Elev= 30
  4365.5 1777.32  4683.2 1778.18  4746.5 1778.26  4799.0 1777.05  4867.3 1777.13
  4923.4 1775.89  4951.8 1774.30  4959.2 1770.30  4965.9 1770.76  4973.4 1764.75
  4987.6 1763.32  4994.3 1764.26  4995.6 1763.32  4996.1 1762.82  5003.9 1762.82
  5004.4 1763.32  5008.5 1769.02  5009.7 1769.29  5016.0 1770.69  5022.7 1770.70
  5036.9 1773.74  5043.7 1773.37  5072.1 1775.65  5100.5 1774.91  5122.1 1776.21
  5143.0 1776.03  5185.6 1778.67  5220.5 1779.35  5342.0 1780.37  5405.8 1780.23
#Mann=6,-1,0
  4365.5   0.045       0  4683.2    0.07       0  4799.0   0.035       0
  4995.6   0.035       0  5004.4   0.035       0  5009.7    0.07       0
Bank Sta=4995.6,5004.4
Exp/Cntr=0.3,0.1

Type RM Length L Ch R = 1,1120,377,377,377
BEGIN DESCRIPTION:
Elm 01 17 2.25
END DESCRIPTION:
XS GIS Cut Line= 3
      1569203.12      6830772.63      1569818.36      6830216.22
      1569949.90      6830052.82
#Sta/Elev= 30
  4230.1 1776.22  4575.7 1777.11  4712.7 1777.24  4849.6 1777.25  4881.1 1776.67
  4914.4 1775.55  4928.6 1773.21  4935.4 1770.44  4942.8 1772.47  4949.6 1772.17
  4957.0 1776.06  4963.8 1773.13  4971.2 1772.41  4978.0 1763.88  4985.4 1763.00
  4992.2 1765.03  4995.6 1763.00  4996.1 1762.50  5004.5 1763.00  5006.4 1769.88
  5013.8 1769.73  5020.5 1773.00  5034.7 1767.51  5041.6 1768.03  5054.6 1772.42
  5063.0 1772.76  5077.4 1776.61  5134.4 1774.66  5184.6 1777.63  5269.4 1777.62
#Mann=7,-1,0
  4230.1   0.045       0  4575.7    0.07       0  4712.7   0.045       0
  4849.6   0.035       0  4881.1    0.07       0  4995.6    0.07       0
  5004.5    0.07       0
Bank Sta=4995.6,5004.5
Exp/Cntr=0.3,0.1

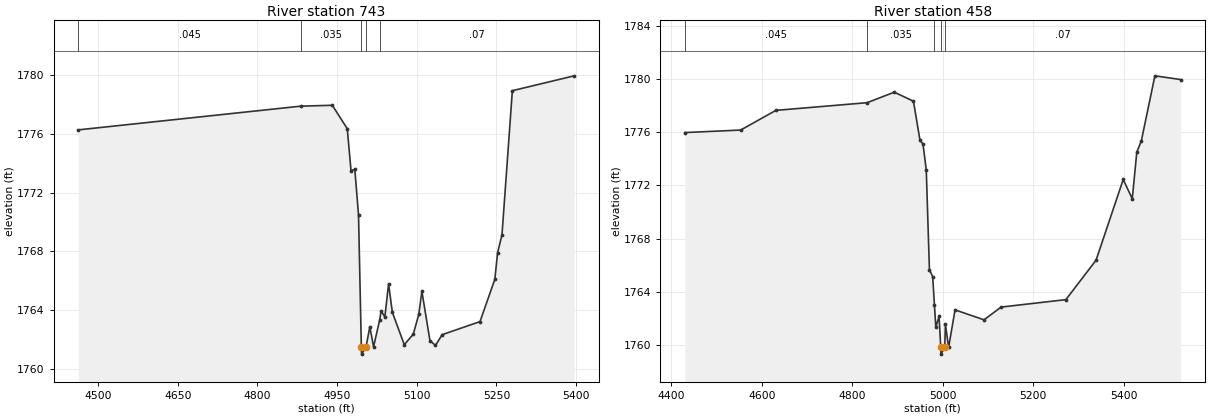
Type RM Length L Ch R = 1,743,285,285,285
BEGIN DESCRIPTION:
Elm 01 17 2.2
END DESCRIPTION:
XS GIS Cut Line= 3
      1569562.56      6830921.91      1569985.76      6830499.57
      1570082.38      6830177.86
#Sta/Elev= 30
  4462.6 1776.26  4881.5 1777.87  4940.9 1777.93  4969.1 1776.34  4976.2 1773.47
  4983.3 1773.59  4990.3 1770.47  4995.6 1761.53  4996.1 1761.03  5004.5 1761.53
  5011.6 1762.89  5018.6 1761.53  5030.2 1763.36  5032.8 1763.96  5039.9 1763.56
  5046.9 1765.80  5054.0 1763.87  5076.5 1761.67  5093.5 1762.39  5103.9 1763.75
  5109.6 1765.30  5124.8 1761.95  5135.2 1761.62  5147.8 1762.35  5219.1 1763.24
  5247.0 1766.11  5252.2 1767.91  5260.5 1769.14  5280.0 1778.92  5396.4 1779.93
#Mann=5,-1,0
  4462.6   0.045       0  4881.5   0.035       0  4995.6   0.035       0
  5004.5   0.035       0  5030.2    0.07       0
Bank Sta=4995.6,5004.5
Exp/Cntr=0.3,0.1

Type RM Length L Ch R = 1,458,0,0,0
BEGIN DESCRIPTION:
Elm 01 17 2.0
END DESCRIPTION:
XS GIS Cut Line= 3
      1569696.13      6831183.75      1570152.23      6830708.30
      1570146.86      6830271.08
#Sta/Elev= 30
  4429.8 1775.97  4553.3 1776.16  4631.2 1777.64  4833.0 1778.22  4892.9 1779.01
  4935.3 1778.33  4949.5 1775.43  4956.4 1775.09  4963.6 1773.17  4970.6 1765.64
  4977.8 1765.13  4981.7 1762.98  4984.7 1761.32  4991.9 1762.14  4995.6 1759.80
  4996.1 1759.30  5004.5 1759.80  5005.9 1761.55  5013.0 1759.80  5027.2 1762.63
  5091.3 1761.88  5129.0 1762.84  5272.2 1763.40  5339.0 1766.37  5399.0 1772.44
  5419.0 1770.99  5429.0 1774.49  5439.0 1775.34  5469.0 1780.24  5525.9 1779.96
#Mann=5,-1,0
  4429.8   0.045       0  4833.0   0.035       0  4981.7    0.07       0
  4995.6    0.07       0  5004.5    0.07       0
Bank Sta=4995.6,5004.5
Exp/Cntr=0.3,0.1

Chan Stop Cuts=-1