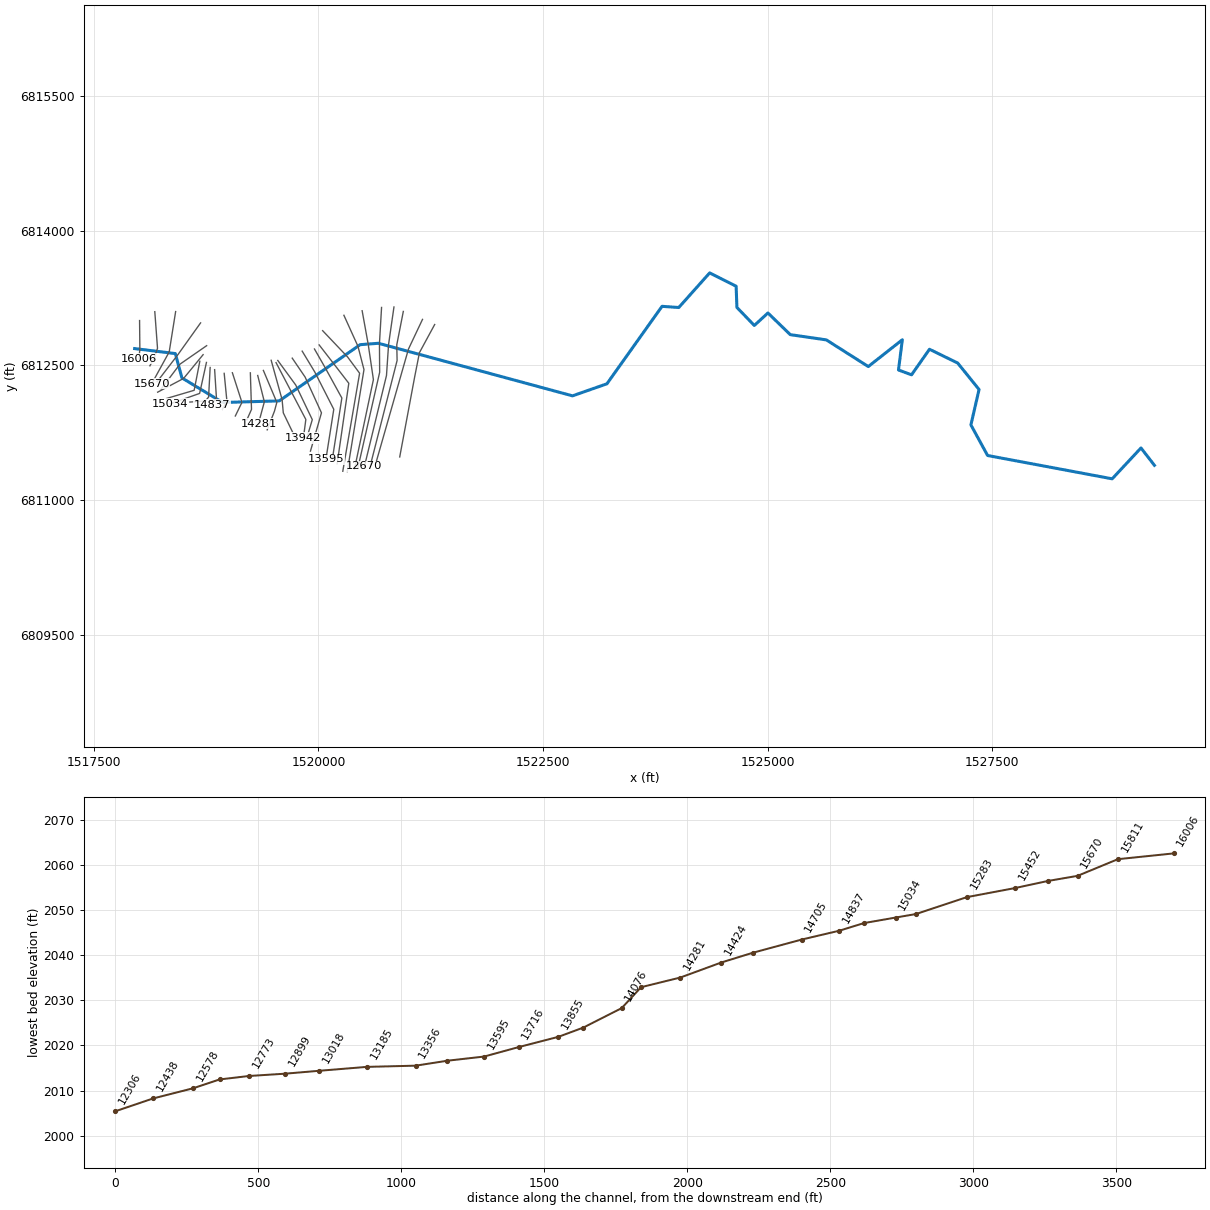
--- Elm 01 20.prj (project) ---

Proj Title=Elm 01 20 Base Level Engineering
Current Plan=p01
Default Exp/Contr=0.3,0.1
English Units
Geom File=g01
Flow File=f01
Plan File=p01
Y Axis Title=Elevation
X Axis Title(PF)=Main Channel Distance
X Axis Title(XS)=Station
BEGIN DESCRIPTION:
Elm 01 20
END DESCRIPTION:
DSS File=dss
DSS Export Rating Curves= 0
DSS Export Rating Curve Sorted= 0
DSS Export Volume Flow Curves= 0
DXF OffsetX= 0
DXF OffsetY= 0
DXF ScaleX= 1
DXF ScaleY= 10

--- Elm 01 20.p01 (plan) ---

Plan Title=Multiple Run
Program Version=4.10
Short Identifier=Multiple Run
Geom File=g01
Flow File=f01
Subcritical Flow
K Sum by GR= 0
Std Step Tol= 0.01
Critical Tol= 0.01
Num of Std Step Trials= 20
Max Error Tol= 0.3
Flow Tol Ratio= 0.001
Split Flow NTrial= 30
Split Flow Tol= 0.02
Split Flow Ratio= 0.02
Log Output Level= 0
Friction Slope Method= 1
Unsteady Friction Slope Method= 2
Unsteady Bridges Friction Slope Method= 1
Parabolic Critical Depth
Global Vel Dist= 1 , 1 , 1
Global Log Level= 0
CheckData=True
Encroach Param=-1 ,0,0, 0
BEGIN DESCRIPTION:
Multiple Run
END DESCRIPTION:
Computation Interval=1HOUR
Output Interval=1HOUR
Run HTab= 0
Run UNet= 0
Run PostProcess= 0
Run WQNet= 0
UNET Theta= 1
UNET Theta Warmup= 1
UNET ZTol= 0.02
UNET ZSATol= 0.05
UNET MxIter= 20
UNET MaxInSteps= 0
UNET DtIC= 0
UNET DtMin= 0
UNET MaxCRTS= 20
UNET WFStab= 2
UNET SFStab= 1
UNET WFX= 1
UNET SFX= 1
UNET DSS MLevel= 4
UNET DZMax Abort= 100
UNET Convert EG Bridges= 0
UNET Use Existing IB Tables=-1
UNET Froude Reduction=False
UNET Froude Limit= 1
UNET Froude Power= 10
UNET Time Slicing=0,0, 5
UNET Junction Losses=0
Instantaneous Interval=1HOUR
DSS File=dss
Write IC File= 0
Write IC File at Sim End=0
Echo Input=False
Echo Parameters=False
Echo Output=False
Write Detailed= 0
WQ AD Non Conservative
WQ ULTIMATE=-1
WQ Max Comp Step=1HOUR
WQ Output Interval=15MIN
WQ Output Selected Increments= 0
WQ Output face flow=0
WQ Output face velocity=0
WQ Output face area=0
WQ Output face dispersion=0
WQ Output cell volume=0
WQ Output cell surface area=0
WQ Output cell continuity=0
WQ Output cumulative cell continuity=0
WQ Output face conc=0
WQ Output face dconc_dx=0
WQ Output face courant=0
WQ Output face peclet=0
WQ Output face adv mass=0
WQ Output face disp mass=0
WQ Output cell mass=0
WQ Output cell source sink temp=0
WQ Output cell source sink nsm=0
WQ Output MaxMinRange=-1
WQ Daily Max Min Mean=-1
WQ Daily Range=0
WQ Daily Time=0
WQ Create Restart=0
WQ Fixed Restart=0
WQ System Summary=0
WQ Use Fixed Temperature=0
Sorting and Armoring Iterations= 10
XS Update Threshold= 0.02
Hydraulics Update Threshold= 0.02
Energy Slope Method= 1
Volume Change Method= 0
XS Weighting Method= 0
Number of US Weighted Cross Sections= 1
Number of DS Weighted Cross Sections= 1
Upstream XS Weight=0.25
Main XS Weight=0.5
Downstream XS Weight=0.25
Number of DS XS's Weighted with US Boundary= 1
Upstream Boundary Weight= 1
Weight of XSs Associated with US Boundary= 0
Number of US XS's Weighted with DS Boundary= 1
Downstream Boundary Weight= 0.5
Weight of XSs Associated with DS Boundary= 0.5
Sediment Output Level= 4
Mass or Volume Output= 0
Output Increment Type= 1
Profile and TS Output Increment= 10
XS Output Flag= 0
XS Output Increment= 10
Disregard all LS=0
Disregard all Conn=0
Disregard all Breaches=0
Disregard all Pumps=0

--- Elm 01 20.f01 (steady flow) ---

Flow Title=Multiple
Number of Profiles=7
Profile Names=10-year,25-year,50-year,1pct_min,100-year,1pct_plu,500-year
River Rch & RM= Elm 01 20,Reach-1,16006
     231     324     403     311     498     686     772
River Rch & RM= Elm 01 20,Reach-1,8115
     405     587     745     587     940    1290    1520
River Rch & RM= Elm 01 20,Reach-1,6785
     396     568     715     558     894    1230    1420
Boundary for River Rch & Prof#=Elm 01 20,Reach-1,1
Up Type=0
Dn Type=3
Dn Slope=0.005
Boundary for River Rch & Prof#=Elm 01 20,Reach-1,2
Up Type=0
Dn Type=3
Dn Slope=0.005
Boundary for River Rch & Prof#=Elm 01 20,Reach-1,3
Up Type=0
Dn Type=3
Dn Slope=0.005
Boundary for River Rch & Prof#=Elm 01 20,Reach-1,4
Up Type=0
Dn Type=3
Dn Slope=0.005
Boundary for River Rch & Prof#=Elm 01 20,Reach-1,5
Up Type=0
Dn Type=3
Dn Slope=0.005
Boundary for River Rch & Prof#=Elm 01 20,Reach-1,6
Up Type=0
Dn Type=3
Dn Slope=0.005
Boundary for River Rch & Prof#=Elm 01 20,Reach-1,7
Up Type=0
Dn Type=3
Dn Slope=0.005

--- Elm 01 20.g01 (geometry) ---

Geom Title=Existing Conditions
Program Version=4.10

River Reach=Elm 01 20       ,Reach-1
Reach XY= 30
        1517955.        6812688.      1518407.71       6812632.6
      1518481.17      6812361.13      1518934.87      6812087.68
      1519563.92      6812105.34      1520465.35      6812731.78
      1520667.85      6812747.18       1522828.4      6812161.62
      1523211.21      6812295.81      1523824.63      6813158.68
      1524011.06      6813145.48      1524354.78      6813531.01
      1524649.45      6813382.41        1524658.      6813146.35
      1524851.83      6812945.51      1525003.24       6813084.7
      1525252.01      6812843.47      1525653.35      6812784.83
      1526120.36      6812487.89      1526499.16      6812786.51
      1526456.38      6812449.58      1526601.78      6812395.87
      1526801.38      6812680.53      1527115.37      6812527.02
      1527353.02      6812232.33       1527262.3      6811837.91
      1527448.26      6811497.13      1528834.87       6811237.6
      1529155.24      6811581.03        1529305.        6811388.

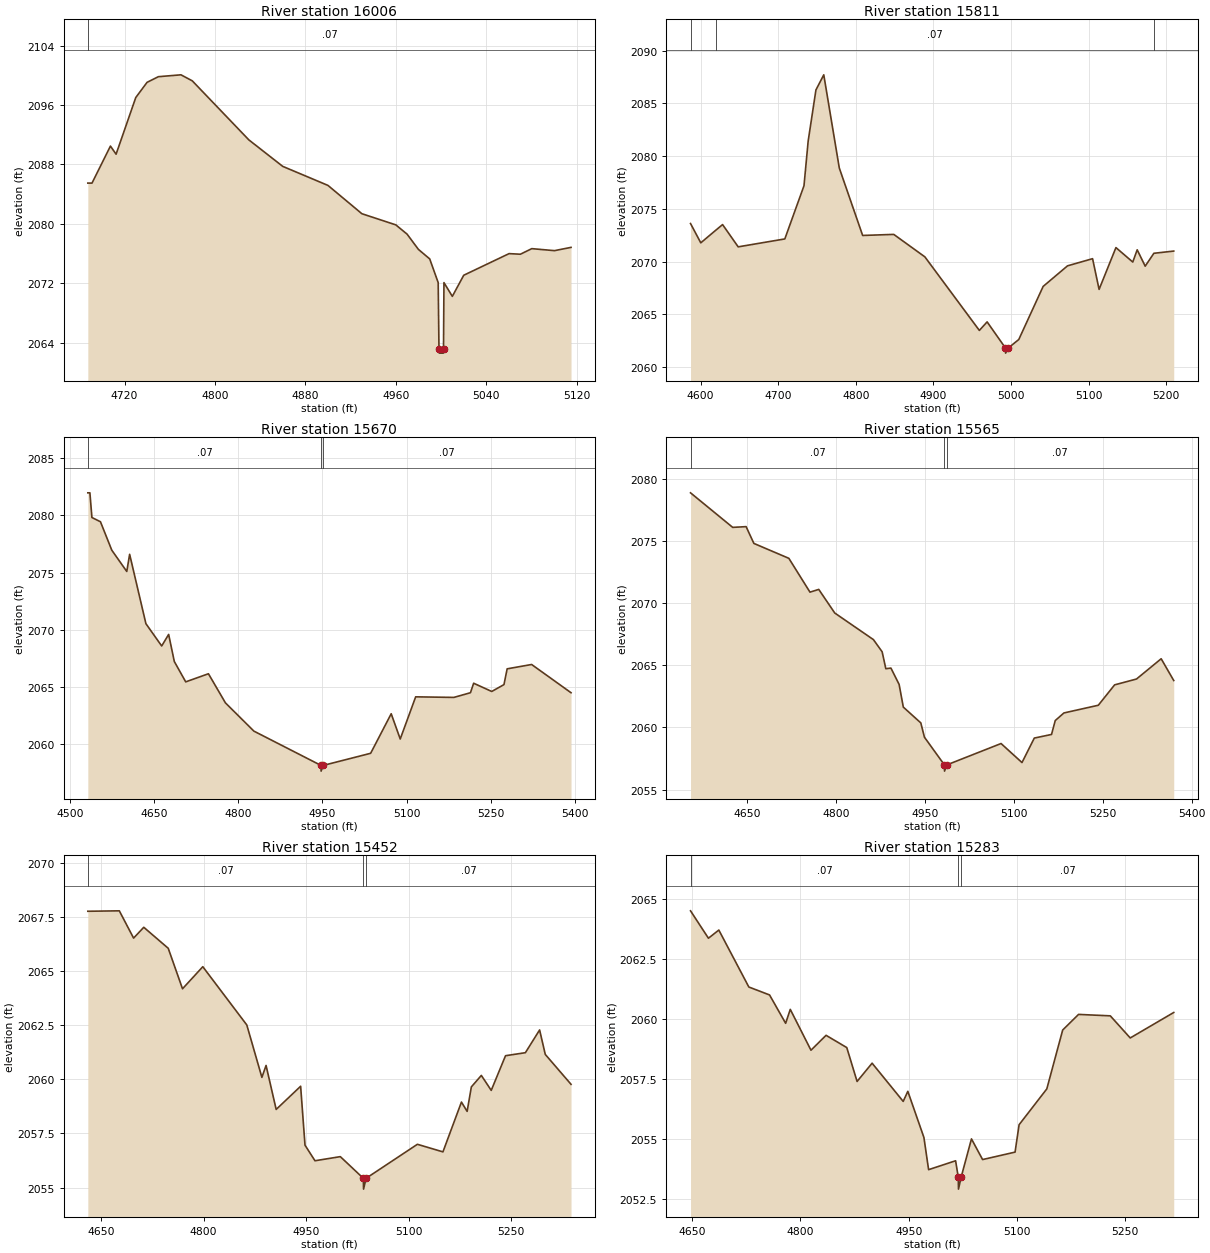
Type RM Length L Ch R = 1 ,16006   ,195,195,195
BEGIN DESCRIPTION:
Elm 01 20 15874.147
END DESCRIPTION:
XS GIS Cut Line= 3
      1518009.78      6813000.38      1518012.88      6812687.89
      1518003.23       6812573.4
#Sta/Elev= 30
  4687.5 2085.49  4691.2 2085.49  4707.5 2090.47  4712.5 2089.38  4729.9    2097
  4739.9 2099.05  4749.9 2099.81  4769.9 2100.06  4779.9 2099.25  4829.9 2091.31
  4859.9 2087.74  4899.9 2085.18  4929.9 2081.37  4959.9 2079.87  4969.9 2078.62
  4979.9 2076.57  4989.9 2075.29  4997.4  2072.1  4998.1 2063.11  4998.4 2062.61
  5001.9 2062.61  5002.1 2063.11  5002.5  2072.1  5009.9 2070.25    5020 2073.09
  5060.1    2076  5070.1 2075.92  5080.2 2076.67  5100.2  2076.4  5114.9 2076.84
#Mann= 1 ,-1 , 0
  4687.5     .07       0
Bank Sta=4998.1,5002.1
XS Rating Curve= 0 ,0
Exp/Cntr=0.3,0.1

Type RM Length L Ch R = 1 ,15811   ,141,141,141
BEGIN DESCRIPTION:
Elm 01 20 15810.39
END DESCRIPTION:
XS GIS Cut Line= 4
      1518179.26      6813099.21      1518209.32      6812692.16
      1518178.17      6812592.31      1518124.64      6812496.28
#Sta/Elev= 30
    4587 2073.61  4600.2 2071.78  4619.6 2072.98  4628.3 2073.51  4648.4  2071.4
  4708.5 2072.15  4733.2 2077.19  4738.6 2081.43  4748.6 2086.27  4758.7  2087.7
  4778.7 2078.87  4808.8 2072.48  4848.9 2072.58    4889 2070.45  4959.2 2063.48
  4969.2 2064.29  4992.7 2061.83    4993 2061.33  4996.7 2061.83    5010 2062.62
  5041.4 2067.65  5072.8  2069.6  5105.1 2070.28  5113.5 2067.37  5135.2 2071.33
  5156.9 2069.96  5162.6 2071.12  5172.9 2069.57  5184.1 2070.79  5209.7    2071
#Mann= 3 ,-1 , 0
    4587     .16       0  4619.6     .07       0  5184.1     .16       0
Bank Sta=4992.7,4996.7
XS Rating Curve= 0 ,0
Exp/Cntr=0.3,0.1

Type RM Length L Ch R = 1 ,15670   ,105,105,105
BEGIN DESCRIPTION:
Elm 01 20 15670.28
END DESCRIPTION:
XS GIS Cut Line= 3
      1518411.15      6813100.19      1518339.53      6812650.93
      1518144.23      6812295.03
#Sta/Elev= 30
  4532.1 2081.98  4535.8 2081.98  4539.4 2079.82  4554.6 2079.45  4574.8 2076.96
  4601.5  2075.1  4606.6  2076.6  4635.6 2070.53  4663.7 2068.58  4676.1 2069.59
  4686.2 2067.22  4706.5 2065.44    4747 2066.15  4777.3  2063.6    4828 2061.13
  4947.5 2058.13  4947.7 2057.63  4951.5 2058.13    5036 2059.19  5072.6 2062.65
  5088.7 2060.44  5116.2 2064.13  5184.3 2064.08  5213.8 2064.49  5219.5 2065.32
  5251.7  2064.6  5273.5  2065.2  5279.2 2066.58  5322.8 2066.96    5393 2064.49
#Mann= 3 ,-1 , 0
  4532.1     .07       0  4947.5     .07       0  4951.5     .07       0
Bank Sta=4947.5,4951.5
XS Rating Curve= 0 ,0
Exp/Cntr=0.3,0.1

Type RM Length L Ch R = 1 ,15565   ,113,113,113
BEGIN DESCRIPTION:
Elm 01 20 15564.73
END DESCRIPTION:
XS GIS Cut Line= 3
      1518688.93      6812974.28      1518435.02      6812618.38
        1518205.      6812318.91
#Sta/Elev= 30
    4555 2078.87  4626.1 2076.09  4648.7 2076.15  4661.8  2074.8  4720.8  2073.6
  4756.4 2070.88  4771.2  2071.1  4798.2  2069.2  4863.4 2067.06  4878.1 2066.08
  4884.3 2064.72  4892.9 2064.77  4906.7 2063.46  4913.8 2061.63  4943.3 2060.36
  4949.4 2059.21  4983.1 2056.98  4983.3 2056.48  4987.1 2056.98  5078.6  2058.7
  5113.9 2057.17  5134.7 2059.14  5163.7 2059.43    5170 2060.55  5184.6 2061.16
  5242.6 2061.78  5270.1 2063.42    5307 2063.89  5348.6 2065.52  5369.8 2063.77
#Mann= 3 ,-1 , 0
    4555     .07       0  4983.1     .07       0  4987.1     .07       0
Bank Sta=4983.1,4987.1
XS Rating Curve= 0 ,0
Exp/Cntr=0.3,0.1

Type RM Length L Ch R = 1 ,15452   ,169,169,169
BEGIN DESCRIPTION:
Elm 01 20 15452.35
END DESCRIPTION:
XS GIS Cut Line= 3
      1518756.21      6812720.38      1518458.89      6812514.21
      1518250.55       6812238.6
#Sta/Elev= 30
  4630.6 2067.76  4676.7 2067.78  4697.6 2066.52  4712.5 2067.02  4748.3 2066.05
  4769.2 2064.18  4798.9  2065.2  4863.3 2062.51  4885.4 2060.09  4891.5 2060.64
  4906.3 2058.61  4942.1 2059.68  4948.5 2056.96  4963.1 2056.24  5000.2 2056.43
  5033.9 2055.43  5034.2 2054.93  5037.9 2055.43    5113    2057  5150.4 2056.65
  5177.5 2058.95  5185.8 2058.52    5192 2059.65  5206.6 2060.18  5221.1 2059.49
    5242 2061.09  5271.1 2061.23  5291.9 2062.28  5300.2 2061.15  5337.9 2059.77
#Mann= 3 ,-1 , 0
  4630.6     .07       0  5033.9     .07       0  5037.9     .07       0
Bank Sta=5033.9,5037.9
XS Rating Curve= 0 ,0
Exp/Cntr=0.3,0.1

Type RM Length L Ch R = 1 ,15283   ,178,178,178
BEGIN DESCRIPTION:
Elm 01 20 15282.89
END DESCRIPTION:
XS GIS Cut Line= 3
      1518717.12      6812620.53      1518500.12      6812355.79
      1518210.92      6812202.55
#Sta/Elev= 30
  4647.7 2064.49  4672.5 2063.35  4686.9 2063.69  4728.5 2061.32  4757.2 2060.99
  4779.5 2059.81  4785.9 2060.39  4814.6 2058.69  4835.5 2059.31  4864.2  2058.8
  4878.5 2057.39  4899.3 2058.15  4942.4 2056.56  4948.8 2056.98  4971.1 2055.06
  4977.6 2053.72    5015 2054.09  5018.7 2053.41    5019 2052.91  5022.7 2053.41
    5037    2055  5052.4 2054.14  5097.4 2054.45    5103 2055.59  5141.4 2057.08
  5163.4 2059.53  5185.4 2060.18  5229.4 2060.12    5257  2059.2  5317.3 2060.26
#Mann= 3 ,-1 , 0
  4647.7     .07       0  5018.7     .07       0  5022.7     .07       0
Bank Sta=5018.7,5022.7
XS Rating Curve= 0 ,0
Exp/Cntr=0.3,0.1

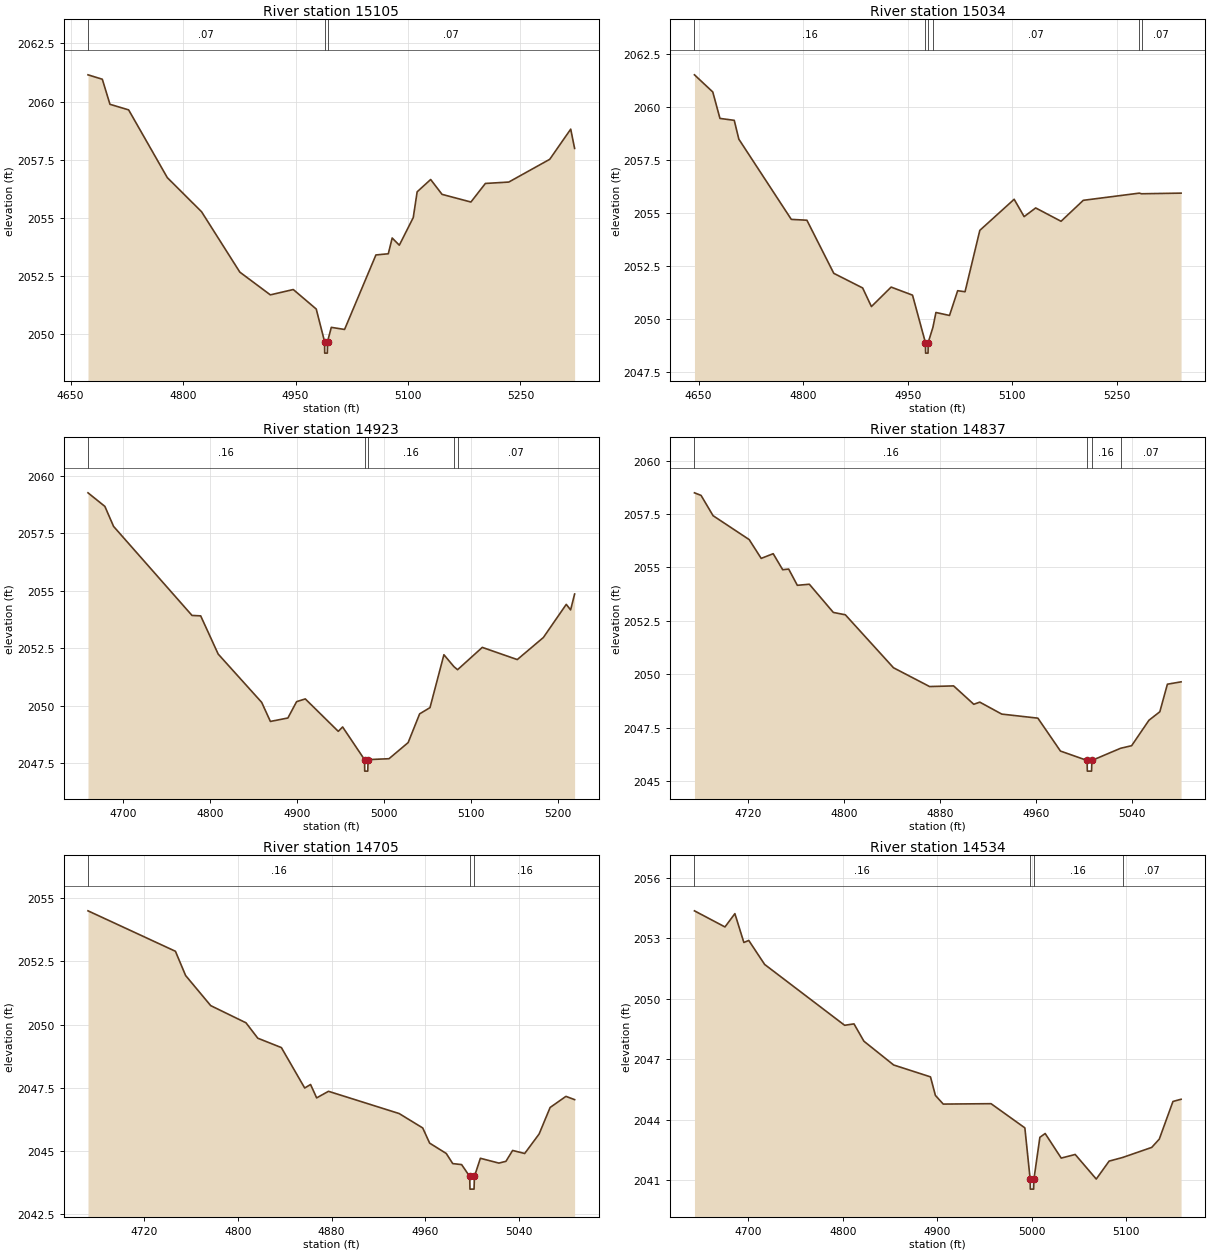
Type RM Length L Ch R = 1 ,15105   ,71,71,71
BEGIN DESCRIPTION:
Elm 01 20 15104.94
END DESCRIPTION:
XS GIS Cut Line= 3
      1518680.24      6812546.75      1518617.31      6812223.41
      1518310.84      6812132.76
#Sta/Elev= 30
  4673.2 2061.15  4692.3 2060.96  4702.5 2059.88  4727.4 2059.64    4779 2056.72
  4824.7 2055.25  4875.7 2052.65  4916.4 2051.67    4947  2051.9  4977.6 2051.06
  4988.7 2049.66  4988.9 2049.16  4992.4 2049.16  4992.7 2049.66  4997.7 2050.27
  5015.4 2050.18  5057.2 2053.39  5073.7 2053.44  5078.9 2054.12  5088.4 2053.81
    5107    2055  5112.2 2056.11  5130.2 2056.64  5145.4    2056  5183.9 2055.67
  5203.2 2056.47  5234.4 2056.53    5289 2057.51    5317 2058.81  5322.2 2057.98
#Mann= 3 ,-1 , 0
  4673.2     .07       0  4988.7     .07       0  4992.7     .07       0
Bank Sta=4988.7,4992.7
XS Rating Curve= 0 ,0
Exp/Cntr=0.3,0.1

Type RM Length L Ch R = 1 ,15034   ,111,111,111
BEGIN DESCRIPTION:
Elm 01 20 15033.75
END DESCRIPTION:
XS GIS Cut Line= 3
      1518754.02      6812533.72      1518678.07      6812188.69
      1518352.58      6812073.68
#Sta/Elev= 30
    4644 2061.53  4670.3 2060.72  4680.6 2059.47  4701.1 2059.38  4707.7 2058.49
    4783  2054.7  4805.4 2054.66    4844 2052.15  4885.4 2051.46    4898 2050.58
  4926.3  2051.5    4957 2051.12  4975.5 2048.88  4975.8 2048.38  4979.3 2048.38
  4979.5 2048.88  4986.3  2049.6  4990.6  2050.3  5010.1 2050.16  5021.8 2051.33
  5032.4 2051.28  5053.6 2054.18  5102.9 2055.65  5117.2 2054.83  5133.8 2055.24
  5170.2 2054.61  5202.1  2055.6  5282.6 2055.94  5285.7 2055.91  5342.5 2055.94
#Mann= 6 ,-1 , 0
    4644     .16       0  4975.5     .07       0  4979.5     .16       0
  4986.3     .07       0  5282.6    .045       0  5285.7     .07       0
Bank Sta=4975.5,4979.5
XS Rating Curve= 0 ,0
Exp/Cntr=0.3,0.1

Type RM Length L Ch R = 1 ,14923   ,86,86,86
BEGIN DESCRIPTION:
Elm 01 20 14932.05
END DESCRIPTION:
XS GIS Cut Line= 4
      1518795.26      6812477.35       1518777.9      6812147.45
      1518741.37      6812104.67      1518569.22       6812092.4
#Sta/Elev= 30
  4659.8 2059.25  4679.2 2058.66  4689.2 2057.79  4779.3 2053.92  4789.3  2053.9
  4809.4 2052.24  4859.4 2050.14  4869.4 2049.31  4889.5 2049.46  4899.5 2050.17
  4909.5 2050.29  4947.4 2048.88  4952.4 2049.07  4977.6 2047.65  4977.8 2047.15
  4981.3 2047.15  4981.6 2047.65  5005.7 2047.69  5027.7 2048.39  5040.9 2049.64
  5052.8 2049.91  5068.8 2052.21  5080.4 2051.69  5084.5 2051.56  5112.9 2052.53
  5153.1    2052  5183.1 2052.96  5209.4  2054.4  5214.4 2054.16    5219 2054.85
#Mann= 5 ,-1 , 0
  4659.8     .16       0  4977.6     .07       0  4981.6     .16       0
  5080.4    .045       0  5084.5     .07       0
Bank Sta=4977.6,4981.6
XS Rating Curve= 0 ,0
Exp/Cntr=0.3,0.1

Type RM Length L Ch R = 1 ,14837   ,132,132,132
BEGIN DESCRIPTION:
Elm 01 20 14836.94
END DESCRIPTION:
XS GIS Cut Line= 3
      1518845.17      6812453.48      1518864.71      6812145.28
      1518814.35      6812062.86
#Sta/Elev= 30
  4675.2 2058.49  4680.7 2058.37  4690.7 2057.42  4720.8  2056.3  4730.8 2055.42
  4740.8 2055.64  4748.7 2054.89  4753.7 2054.92  4760.9 2054.16  4770.9 2054.21
  4790.9 2052.89  4800.9 2052.78    4841  2050.3  4871.1 2049.42  4891.1 2049.45
  4907.9 2048.59  4912.9 2048.69  4931.2 2048.13  4961.3 2047.94  4980.1  2046.4
  5002.3 2045.96  5002.5 2045.46    5006 2045.46  5006.3 2045.96  5030.2 2046.53
  5039.4 2046.65  5053.8 2047.84  5062.9 2048.24  5069.2 2049.53  5080.6 2049.64
#Mann= 4 ,-1 , 0
  4675.2     .16       0  5002.3     .07       0  5006.3     .16       0
  5030.2     .07       0
Bank Sta=5002.3,5006.3
XS Rating Curve= 0 ,0
Exp/Cntr=0.3,0.1

Type RM Length L Ch R = 1 ,14705   ,171,171,171
BEGIN DESCRIPTION:
Elm 01 20 14708.59
END DESCRIPTION:
XS GIS Cut Line= 3
      1518951.51       6812412.2      1518981.89      6812101.88
      1518931.66      6812011.51
#Sta/Elev= 30
  4672.1  2054.5  4746.7  2052.9  4755.4 2051.94  4776.8 2050.75  4806.9 2050.07
    4817 2049.46  4837.1 2049.09    4857 2047.49    4862 2047.63  4867.2  2047.1
  4877.3 2047.36  4937.6 2046.48  4957.7 2045.91  4963.6 2045.31  4977.8  2044.9
  4983.3  2044.5  4990.9 2044.46  4997.8 2043.99    4998 2043.49  5001.5 2043.49
  5001.8 2043.99  5006.9 2044.71  5022.7 2044.52  5028.7 2044.59  5034.4 2045.02
  5044.7  2044.9    5057 2045.67  5066.4 2046.72  5079.9 2047.16  5087.3 2047.03
#Mann= 3 ,-1 , 0
  4672.1     .16       0  4997.8     .07       0  5001.8     .16       0
Bank Sta=4997.8,5001.8
XS Rating Curve= 0 ,0
Exp/Cntr=0.3,0.1

Type RM Length L Ch R = 1 ,14534   ,110,110,110
BEGIN DESCRIPTION:
Elm 01 20 14535.75
END DESCRIPTION:
XS GIS Cut Line= 3
      1519042.65      6812418.74      1519148.99      6812088.86
      1519075.35      6811937.19
#Sta/Elev= 30
  4642.9 2054.37  4675.2 2053.57  4685.7 2054.23  4695.2  2052.8  4700.4  2052.9
  4717.2 2051.71  4801.9 2048.69  4811.8 2048.76  4822.3  2047.9  4853.8 2046.72
  4892.8 2046.13    4898 2045.21  4906.3 2044.78  4956.9  2044.8  4992.7  2043.6
  4998.3 2041.06  4998.5 2040.56    5002 2040.56  5002.3 2041.06  5008.6 2043.13
  5014.2 2043.32  5031.2  2042.1    5046 2042.28  5068.3 2041.06  5081.9 2041.95
  5096.2 2042.13    5127 2042.63    5135 2043.04  5149.5 2044.91  5158.1 2045.02
#Mann= 4 ,-1 , 0
  4642.9     .16       0  4998.3     .07       0  5002.3     .16       0
  5096.2     .07       0
Bank Sta=4998.3,5002.3
XS Rating Curve= 0 ,0
Exp/Cntr=0.3,0.1

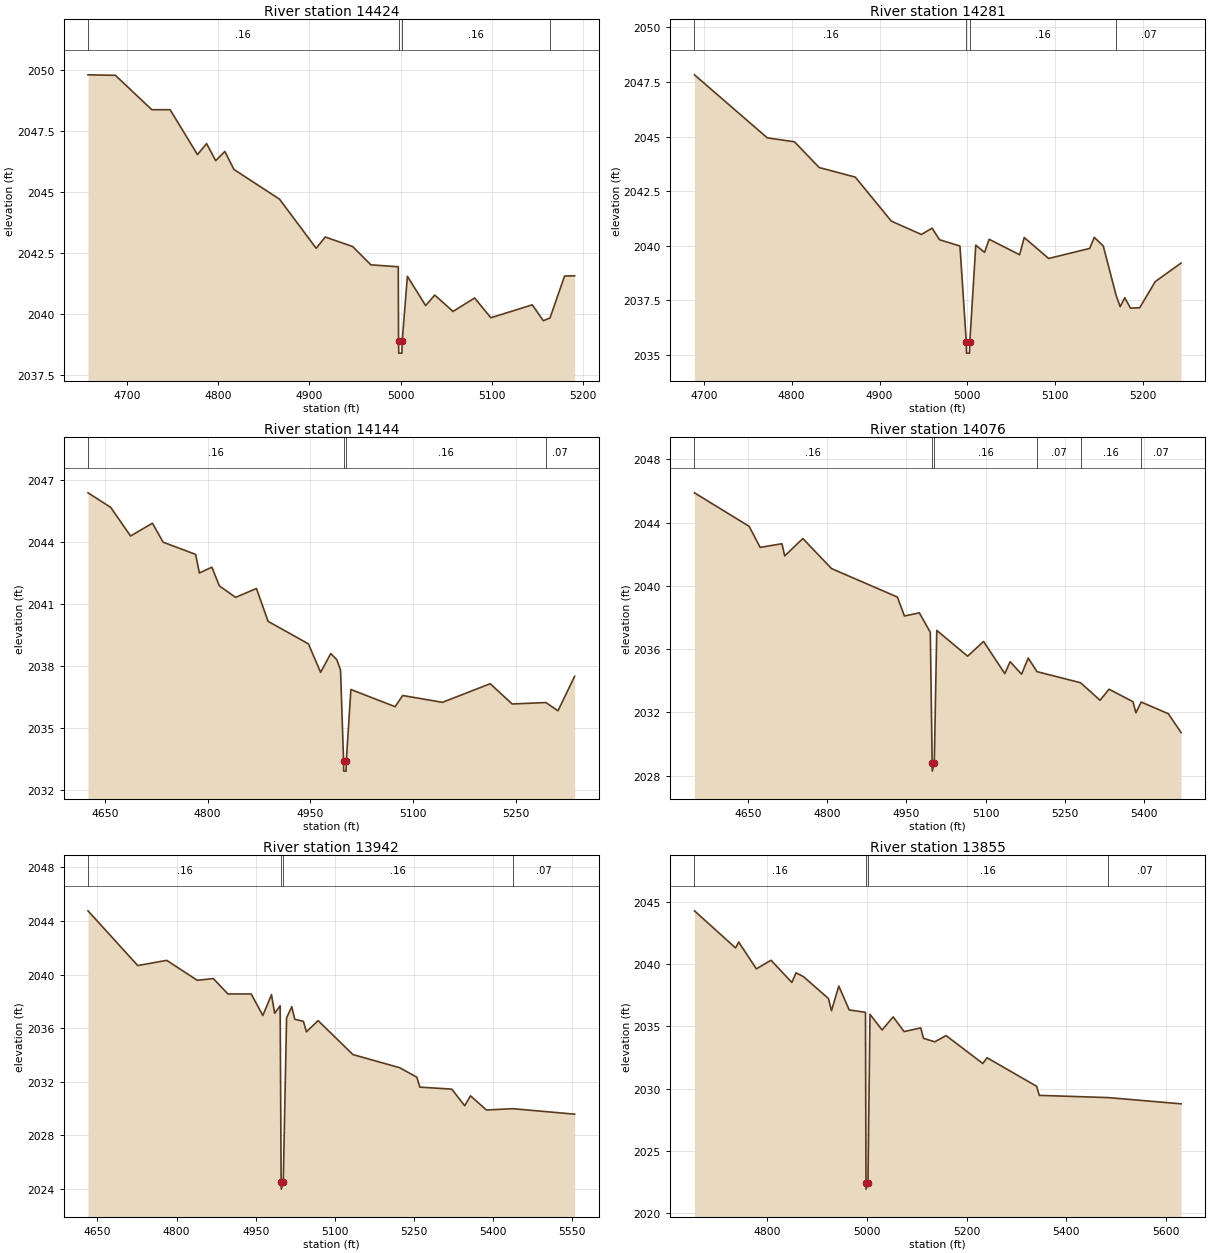
Type RM Length L Ch R = 1 ,14424   ,143,143,143
BEGIN DESCRIPTION:
Elm 01 20 14396.97
END DESCRIPTION:
XS GIS Cut Line= 3
      1519242.76      6812417.94       1519255.5      6812010.82
      1519204.36      6811895.57
#Sta/Elev= 30
  4657.4 2049.81  4687.4 2049.79  4727.4 2048.38  4747.4 2048.38  4777.4 2046.54
  4787.4 2046.99  4797.4 2046.29  4807.4 2046.67  4817.4 2045.93  4867.4 2044.71
  4907.5  2042.7  4917.5 2043.16  4947.5 2042.77  4967.5 2042.02  4997.5 2041.94
  4997.8  2038.9    4998  2038.4  5001.5  2038.4  5001.8  2038.9  5007.5 2041.55
  5027.5 2040.35  5037.5 2040.78  5057.5 2040.11  5081.2 2040.66    5099 2039.85
  5144.4 2040.38  5156.5 2039.73  5163.8 2039.84  5179.8 2041.56  5190.8 2041.57
#Mann= 4 ,-1 , 0
  4657.4     .16       0  4997.8     .07       0  5001.8     .16       0
  5163.8     .07       0
Bank Sta=4997.8,5001.8
XS Rating Curve= 0 ,0
Exp/Cntr=0.3,0.1

Type RM Length L Ch R = 1 ,14281   ,137,137,137
BEGIN DESCRIPTION:
Elm 01 20 14284.86
END DESCRIPTION:
XS GIS Cut Line= 3
      1519324.77      6812388.35      1519398.56      6812095.37
      1519332.89      6811852.52
#Sta/Elev= 30
  4689.4 2047.83  4772.3 2044.94  4803.2 2044.76  4831.3 2043.58  4872.4 2043.14
  4913.5 2041.12  4947.6 2040.51  4959.8  2040.8  4968.2 2040.27  4991.5 2039.98
  4998.7 2035.57  4998.9 2035.07  5002.4 2035.07  5002.7 2035.57  5009.5 2040.02
  5019.5 2039.69  5024.7 2040.29  5059.4 2039.58  5064.6 2040.37  5092.4 2039.41
  5139.1 2039.87  5144.3 2040.38  5154.6 2039.98  5169.1 2037.73  5173.8  2037.2
    5179 2037.61  5185.6 2037.13    5196 2037.15  5213.7 2038.35  5243.1  2039.2
#Mann= 4 ,-1 , 0
  4689.4     .16       0  4998.7     .07       0  5002.7     .16       0
  5169.1     .07       0
Bank Sta=4998.7,5002.7
XS Rating Curve= 0 ,0
Exp/Cntr=0.3,0.1

Type RM Length L Ch R = 1 ,14144   ,68,68,68
BEGIN DESCRIPTION:
Elm 01 20 14143.75
END DESCRIPTION:
XS GIS Cut Line= 4
      1519387.72      6812444.74      1519537.45      6812088.86
      1519511.21       6811991.7      1519430.16      6811783.02
#Sta/Elev= 30
  4625.3  2046.4  4658.4  2045.7  4687.5 2044.31  4719.4 2044.93    4735 2044.01
  4782.5 2043.42  4787.9 2042.52  4806.2  2042.8  4817.1  2041.9  4840.8 2041.34
  4871.3 2041.77  4888.3 2040.18  4947.2 2039.09    4965 2037.71  4979.8 2038.62
  4988.7 2038.32  4994.1 2037.82  4998.5 2033.43  4998.7 2032.93  5002.2 2032.93
  5002.5 2033.43  5009.2 2036.88  5073.8 2036.05  5084.8 2036.59  5142.9 2036.26
  5212.6 2037.16  5244.7 2036.18  5293.9 2036.25  5311.6 2035.85  5335.9 2037.52
#Mann= 4 ,-1 , 0
  4625.3     .16       0  4998.5     .07       0  5002.5     .16       0
  5293.9     .07       0
Bank Sta=4998.5,5002.5
XS Rating Curve= 0 ,0
Exp/Cntr=0.3,0.1

Type RM Length L Ch R = 1 ,14076   ,134,134,134
BEGIN DESCRIPTION:
Elm 01 20 14076.45
END DESCRIPTION:
XS GIS Cut Line= 4
       1519474.5      6812557.66      1519596.04      6812119.24
      1519609.37       6811972.2      1519747.13      6811686.25
#Sta/Elev= 30
  4549.3 2045.88  4652.7 2043.76  4673.5 2042.43  4714.7 2042.66  4719.9 2041.89
  4754.2 2042.99  4808.4 2041.09  4932.9 2039.29  4946.3 2038.09  4974.4 2038.29
  4995.2 2037.06  4998.7 2028.78  4998.9 2028.28  5002.7 2028.78  5007.4 2037.18
  5065.7 2035.55  5095.9 2036.48    5136 2034.45  5146.1  2035.2  5167.7 2034.41
  5180.3 2035.43    5197 2034.57  5279.3 2033.87  5316.1 2032.76  5333.1 2033.46
  5378.4 2032.67  5383.9 2031.97  5393.8 2032.65  5445.2 2031.91  5469.3 2030.72
#Mann= 6 ,-1 , 0
  4549.3     .16       0  4998.7     .07       0  5002.7     .16       0
    5197     .07       0  5279.3     .16       0  5393.8     .07       0
Bank Sta=4998.7,5002.7
XS Rating Curve= 0 ,0
Exp/Cntr=0.3,0.1

Type RM Length L Ch R = 1 ,13942   ,87,87,87
BEGIN DESCRIPTION:
Elm 01 20 13944.72
END DESCRIPTION:
XS GIS Cut Line= 3
      1519528.78      6812531.54      1519860.25      6811898.56
      1519833.28      6811692.24
#Sta/Elev= 30
    4632 2044.76  4726.4 2040.67  4781.3 2041.06  4839.2 2039.57  4869.6  2039.7
  4897.3 2038.55  4941.4 2038.55  4963.5 2036.94  4979.9  2038.5  4985.9  2037.1
  4996.3 2037.67  4998.2 2024.47  4998.5 2023.97  5002.2 2024.47  5008.5 2036.77
  5018.4  2037.6    5024 2036.66  5040.5  2036.5  5046.1 2035.72  5068.2 2036.56
  5134.4 2034.02    5223 2033.04  5255.5 2032.33  5261.1 2031.59  5321.7 2031.44
  5346.2  2030.2  5357.2 2030.94  5387.4 2029.88  5437.3 2029.98  5554.6 2029.57
#Mann= 4 ,-1 , 0
    4632     .16       0  4998.2     .07       0  5002.2     .16       0
  5437.3     .07       0
Bank Sta=4998.2,5002.2
XS Rating Curve= 0 ,0
Exp/Cntr=0.3,0.1

Type RM Length L Ch R = 1 ,13855   ,139,139,139
BEGIN DESCRIPTION:
Elm 01 20 13855.25
END DESCRIPTION:
XS GIS Cut Line= 4
      1519548.28      6812555.46      1519747.95        6812282.
      1519932.16       6811896.5      1519871.64      6811695.25
#Sta/Elev= 30
  4654.3 2044.27  4736.8 2041.29    4743 2041.76  4778.5 2039.61  4807.9  2040.3
  4849.6 2038.52  4858.1 2039.29  4872.8 2038.99    4923 2037.23  4929.1 2036.25
  4943.8 2038.23  4964.7 2036.31  4997.3 2036.12  4998.3 2022.42  4998.6 2021.92
  5002.3 2022.42  5006.4 2035.96  5030.6  2034.7  5052.8 2035.75  5074.9 2034.57
  5108.1 2034.87  5113.7 2034.03  5136.3 2033.75    5159 2034.25  5232.6 2032.01
  5241.2 2032.47  5340.5 2030.18    5346 2029.45  5484.4 2029.27  5630.3 2028.77
#Mann= 4 ,-1 , 0
  4654.3     .16       0  4998.3     .07       0  5002.3     .16       0
  5484.4     .07       0
Bank Sta=4998.3,5002.3
XS Rating Curve= 0 ,0
Exp/Cntr=0.3,0.1

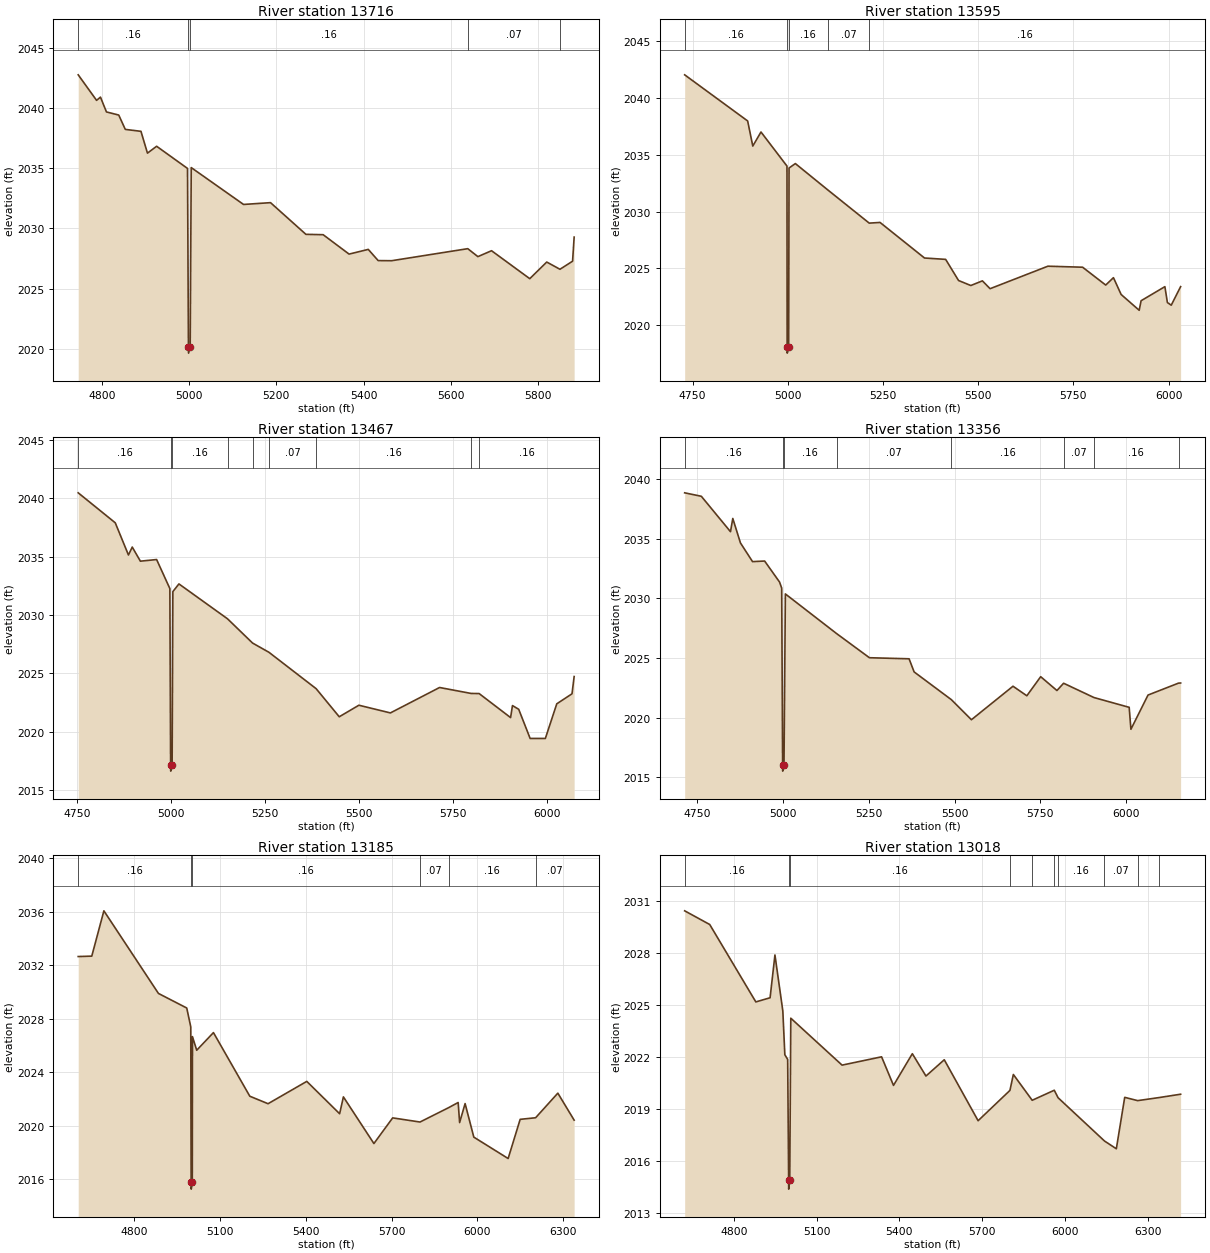
Type RM Length L Ch R = 1 ,13716   ,121,121,121
BEGIN DESCRIPTION:
Elm 01 20 13716.17
END DESCRIPTION:
XS GIS Cut Line= 4
      1519708.87      6812581.51      1519852.12      6812370.98
      1520034.24      6811972.33      1519911.65      6811546.03
#Sta/Elev= 30
  4745.9 2042.74    4788 2040.62  4796.9 2040.89  4810.6 2039.66  4838.8  2039.4
  4853.8 2038.21  4889.7 2038.05  4904.6 2036.24  4925.6 2036.81  4996.4 2034.97
  4998.5 2020.14  4998.8 2019.64  5002.5 2020.14  5004.9 2035.04  5124.8 2031.98
  5186.6 2032.13  5267.7  2029.5  5307.2 2029.47  5366.6 2027.86  5410.6 2028.25
  5433.3 2027.32  5464.1 2027.31  5638.6 2028.31  5661.8 2027.65  5693.1 2028.14
  5780.7 2025.82  5819.6  2027.2  5849.9  2026.6  5878.8 2027.27  5882.4 2029.27
#Mann= 5 ,-1 , 0
  4745.9     .16       0  4998.5     .07       0  5002.5     .16       0
  5638.6     .07       0  5849.9     .16       0
Bank Sta=4998.5,5002.5
XS Rating Curve= 0 ,0
Exp/Cntr=0.3,0.1

Type RM Length L Ch R = 1 ,13595   ,128,128,128
BEGIN DESCRIPTION:
Elm 01 20 13594.55
END DESCRIPTION:
XS GIS Cut Line= 4
      1519819.58      6812659.59      1519958.46      6812429.57
      1520171.23      6812011.69      1520083.35       6811453.7
#Sta/Elev= 30
  4729.2 2042.03  4894.6 2037.97  4908.1 2035.76  4929.6    2037  4997.9    2034
  4998.3 2018.04  4998.6 2017.54  5002.3 2018.04  5003.3 2033.83  5019.9 2034.22
  5105.5 2031.89  5213.9 2028.98  5242.3 2029.04  5359.1 2025.91  5414.6 2025.79
  5448.5 2023.93  5480.7 2023.49  5511.1  2023.9  5531.3 2023.21  5683.2 2025.19
  5774.3  2025.1    5835 2023.53  5855.3 2024.18  5875.5  2022.7  5922.9 2021.31
  5927.9 2022.15  5990.4 2023.39    5997 2021.99  6007.1 2021.76  6031.7 2023.39
#Mann= 5 ,-1 , 0
  4729.2     .16       0  4998.3     .07       0  5002.3     .16       0
  5105.5     .07       0  5213.9     .16       0
Bank Sta=4998.3,5002.3
XS Rating Curve= 0 ,0
Exp/Cntr=0.3,0.1

Type RM Length L Ch R = 1 ,13467   ,111,111,111
BEGIN DESCRIPTION:
Elm 01 20 13467.39
END DESCRIPTION:
XS GIS Cut Line= 4
      1519956.28      6812683.49      1520077.81      6812470.81
       1520261.1       6812137.4      1520154.59      6811452.35
#Sta/Elev= 30
  4753.4 2040.48  4851.9 2037.91    4887 2035.15  4897.1 2035.83  4918.7 2034.62
  4961.9 2034.76  4997.1 2032.27  4999.1 2017.12  4999.4 2016.62  5003.1 2017.12
  5005.1 2032.01  5021.2 2032.67  5150.4 2029.68    5217  2027.6  5260.5 2026.81
    5386 2023.69  5447.5 2021.28  5499.7 2022.27  5583.5 2021.61  5714.3 2023.79
  5798.1 2023.28  5819.4 2023.27  5903.1 2021.21  5908.1 2022.24  5924.7 2021.92
  5955.1 2019.42  5995.5 2019.42  6025.9 2022.39  6066.4 2023.25  6072.1 2024.73
#Mann= 9 ,-1 , 0
  4753.4     .16       0  4999.1     .07       0  5003.1     .16       0
  5150.4     .07       0    5217     .16       0  5260.5     .07       0
    5386     .16       0  5798.1     .07       0  5819.4     .16       0
Bank Sta=4999.1,5003.1
XS Rating Curve= 0 ,0
Exp/Cntr=0.3,0.1

Type RM Length L Ch R = 1 ,13356   ,171,171,171
BEGIN DESCRIPTION:
Elm 01 20 13356.42
END DESCRIPTION:
XS GIS Cut Line= 4
      1520008.39      6812729.03      1520186.32      6812499.02
      1520338.46      6812301.65       1520208.6      6811403.89
#Sta/Elev= 30
  4712.6 2038.86  4761.2 2038.57  4846.3  2035.6    4853 2036.71  4875.3 2034.66
  4910.6 2033.09  4945.9 2033.14  4989.4 2031.38  4995.7 2030.87  4998.4 2016.02
  4998.6 2015.52  5002.4 2016.02  5006.4 2030.38  5155.7 2027.06  5251.7 2025.03
  5367.4 2024.94  5382.1 2023.84  5490.9 2021.51  5549.3 2019.83  5670.6 2022.64
    5711 2021.84  5751.4 2023.44  5798.8 2022.28  5818.3 2022.89    5907 2021.69
  6009.6 2020.87  6014.7 2019.03  6064.6  2021.9  6153.6  2022.9  6159.7 2022.91
#Mann= 8 ,-1 , 0
  4712.6     .16       0  4998.4     .07       0  5002.4     .16       0
  5155.7     .07       0  5490.9     .16       0  5818.3     .07       0
    5907     .16       0  6153.6     .07       0
Bank Sta=4998.4,5002.4
XS Rating Curve= 0 ,0
Exp/Cntr=0.3,0.1

Type RM Length L Ch R = 1 ,13185   ,167,167,167
BEGIN DESCRIPTION:
Elm 01 20 13185.12
END DESCRIPTION:
XS GIS Cut Line= 4
       1520047.4      6812887.51      1520325.21       6812594.5
      1520458.75      6812413.37      1520271.56      6811321.71
#Sta/Elev= 30
  4603.1 2032.65  4650.6 2032.68    4693 2036.07    4884 2029.89  4983.1  2028.8
  4997.2 2027.39  4998.5 2015.75  4998.8 2015.25  5002.5 2015.75  5003.1 2026.66
    5018 2025.64  5076.6 2026.96  5203.9  2022.2  5267.8 2021.64  5403.4 2023.31
  5518.4 2020.89  5531.6 2022.15  5638.4 2018.66  5704.1 2020.58  5799.8 2020.27
  5899.6 2021.34  5933.4 2021.73  5938.5 2020.23  5957.7 2021.65  5988.2 2019.14
  6108.4 2017.54  6150.5 2020.47  6204.6 2020.59  6282.4 2022.43  6339.5 2020.41
#Mann= 6 ,-1 , 0
  4603.1     .16       0  4998.5     .07       0  5002.5     .16       0
  5799.8     .07       0  5899.6     .16       0  6204.6     .07       0
Bank Sta=4998.5,5002.5
XS Rating Curve= 0 ,0
Exp/Cntr=0.3,0.1

Type RM Length L Ch R = 1 ,13018   ,119,119,119
BEGIN DESCRIPTION:
Elm 01 20 13018.47
END DESCRIPTION:
XS GIS Cut Line= 4
      1520283.98       6813058.9      1520440.23      6812713.86
      1520507.35      6812453.76      1520321.47      6811317.96
#Sta/Elev= 30
  4621.5 2030.45  4712.3 2029.66  4879.5 2025.19  4931.2 2025.43  4948.8  2027.9
  4977.4 2024.67  4984.7 2022.14    4995 2021.87  4998.5 2014.88  4998.7 2014.38
  5002.5 2014.88  5006.3 2024.25  5192.2 2021.54  5335.5 2022.02  5378.7 2020.37
    5447  2022.2  5496.4 2020.91  5562.8 2021.85  5685.5 2018.33  5800.9 2020.08
  5813.3    2021  5881.6 2019.51  5961.7 2020.09  5975.3 2019.66  6143.7 2017.16
  6186.7 2016.71  6217.1 2019.68  6264.1 2019.49    6343 2019.67  6419.8 2019.86
#Mann= 10 ,-1 , 0
  4621.5     .16       0  4998.5     .07       0  5002.5     .16       0
  5800.9     .07       0  5881.6     .16       0  5961.7     .07       0
  5975.3     .16       0  6143.7     .07       0  6264.1    .035       0
    6343     .07       0
Bank Sta=4998.5,5002.5
XS Rating Curve= 0 ,0
Exp/Cntr=0.3,0.1

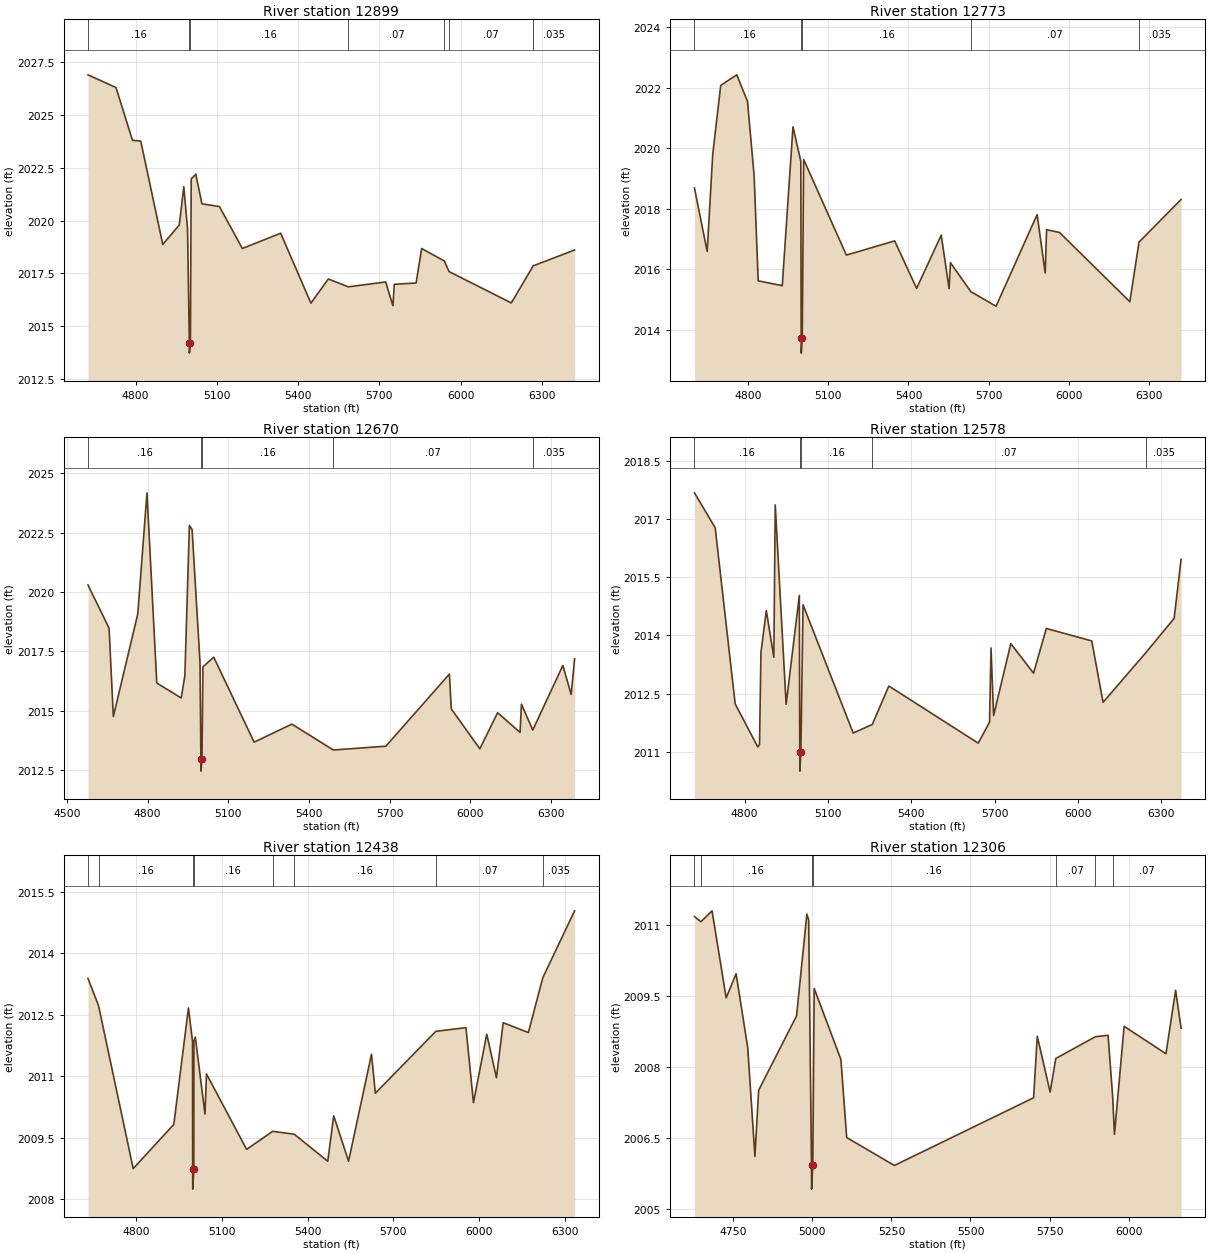
Type RM Length L Ch R = 1 ,12899   ,126,126,126
BEGIN DESCRIPTION:
Elm 01 20 12898.92
END DESCRIPTION:
XS GIS Cut Line= 4
      1520486.89      6813109.68      1520554.59      6812734.69
      1520612.33      6812342.68      1520401.44      6811345.53
#Sta/Elev= 30
  4624.5 2026.88  4727.8 2026.28  4788.8 2023.79  4819.3 2023.75  4900.6 2018.87
  4961.5 2019.79  4978.2  2021.6    4992 2019.62  4998.6 2014.24  4998.9 2013.74
  5002.6 2014.24  5005.5 2021.96  5022.4 2022.19  5045.2 2020.79  5109.8 2020.66
  5194.3 2018.68  5335.8  2019.4  5447.5  2016.1  5511.8 2017.24  5585.6 2016.87
  5723.4  2017.1  5750.2 2015.98  5755.3 2016.99  5835.9 2017.05  5856.3 2018.68
  5939.9 2018.09  5957.4 2017.59  6187.4 2016.11    6268 2017.86    6421 2018.61
#Mann= 7 ,-1 , 0
  4624.5     .16       0  4998.6     .07       0  5002.6     .16       0
  5585.6     .07       0  5939.9     .16       0  5957.4     .07       0
    6268    .035       0
Bank Sta=4998.6,5002.6
XS Rating Curve= 0 ,0
Exp/Cntr=0.3,0.1

Type RM Length L Ch R = 1 ,12773   ,103,103,103
BEGIN DESCRIPTION:
Elm 01 20 12772.59
END DESCRIPTION:
XS GIS Cut Line= 4
      1520703.03      6813146.15      1520679.59      6812745.11
      1520681.92      6812424.14      1520438.24       6811352.5
#Sta/Elev= 30
  4598.8 2018.69  4646.4 2016.59  4667.1 2019.79  4697.1 2022.08  4757.2 2022.43
  4797.3 2021.55  4822.2 2019.09  4837.4 2015.62  4927.5 2015.46  4967.6 2020.71
    4997 2019.57  4998.3 2013.73  4998.6 2013.23  5002.3 2013.73  5007.6 2019.63
  5167.6 2016.47  5348.3 2016.94  5430.4 2015.37  5522.6 2017.13    5552 2015.36
  5557.1 2016.22  5633.8 2015.26  5727.8 2014.78  5881.6 2017.81  5911.8 2015.88
    5917 2017.31  5965.2 2017.22  6228.7 2014.93    6263  2016.9  6420.5 2018.31
#Mann= 5 ,-1 , 0
  4598.8     .16       0  4998.3     .07       0  5002.3     .16       0
  5633.8     .07       0    6263    .035       0
Bank Sta=4998.3,5002.3
XS Rating Curve= 0 ,0
Exp/Cntr=0.3,0.1

Type RM Length L Ch R = 1 ,12670   ,92,92,92
BEGIN DESCRIPTION:
Elm 01 20 12670.25
END DESCRIPTION:
XS GIS Cut Line= 4
      1520841.05      6813151.32      1520781.16      6812734.69
      1520757.92      6812388.44      1520512.26      6811375.45
#Sta/Elev= 30
  4578.3  2020.3  4656.7 2018.48  4672.6 2014.76  4763.5 2019.08  4797.7 2024.18
  4834.2 2016.17  4925.2 2015.54  4938.7 2016.49  4955.5 2022.81  4965.6 2022.63
    4995 2017.03  4998.3 2012.96  4998.5 2012.46  5002.3 2012.96  5005.9 2016.85
    5046 2017.26  5196.3 2013.68  5336.7 2014.44  5490.8 2013.35  5686.3 2013.51
  5922.9 2016.55  5929.8 2015.08  6036.1  2013.4  6102.1 2014.92  6185.7 2014.09
  6190.8 2015.28  6232.9 2014.19  6344.8 2016.91  6375.7 2015.69  6388.6 2017.19
#Mann= 5 ,-1 , 0
  4578.3     .16       0  4998.3     .07       0  5002.3     .16       0
  5490.8     .07       0  6232.9    .035       0
Bank Sta=4998.3,5002.3
XS Rating Curve= 0 ,0
Exp/Cntr=0.3,0.1

Type RM Length L Ch R = 1 ,12578   ,140,140,140
BEGIN DESCRIPTION:
Elm 01 20 12578.32
END DESCRIPTION:
XS GIS Cut Line= 4
      1520945.22      6813101.91       1520872.3      6812729.49
      1520876.03      6812555.47      1520579.87      6811393.78
#Sta/Elev= 30
  4619.3 2017.67    4694 2016.77  4765.9 2012.24  4847.5 2011.13  4853.6  2011.2
  4858.7 2013.56    4878 2014.64  4905.1 2013.44  4910.2 2017.36  4949.4 2012.23
    4997 2015.03  4998.5 2011.01  4998.8 2010.51  5002.5 2011.01  5010.3 2014.79
  5190.9 2011.49  5259.7 2011.71  5319.3  2012.7  5641.2 2011.23    5682 2011.77
  5687.2 2013.68  5696.6 2011.94  5758.5 2013.79  5840.4 2013.03  5886.4 2014.18
    6050 2013.86  6090.8 2012.28  6246.2 2013.57  6346.7 2014.44  6371.7 2015.96
#Mann= 5 ,-1 , 0
  4619.3     .16       0  4998.5     .07       0  5002.5     .16       0
  5259.7     .07       0  6246.2    .035       0
Bank Sta=4998.5,5002.5
XS Rating Curve= 0 ,0
Exp/Cntr=0.3,0.1

Type RM Length L Ch R = 1 ,12438   ,132,132,132
BEGIN DESCRIPTION:
Elm 01 20 12437.41
END DESCRIPTION:
XS GIS Cut Line= 3
      1521158.77      6813013.35      1521002.51      6812682.61
      1520635.49       6811397.8
#Sta/Elev= 30
  4631.9 2013.39  4668.7 2012.73    4790 2008.75  4932.1 2009.83  4983.2 2012.67
  4997.5 2011.85    4998 2008.75  4998.3 2008.25    5002 2008.75  5002.3 2011.85
  5007.3 2011.96  5041.1 2010.08  5046.3 2011.06  5186.7 2009.22  5277.7 2009.66
  5353.2 2009.59  5470.5 2008.93  5491.3 2010.04  5543.3 2008.93  5623.5 2011.54
  5636.9 2010.59  5848.5  2012.1  5953.8 2012.19  5980.1 2010.36  6026.6 2012.03
  6060.4 2010.97  6084.1 2012.31  6172.2 2012.07  6222.7 2013.41  6333.9 2015.04
#Mann= 8 ,-1 , 0
  4631.9    .035       0  4668.7     .16       0    4998     .07       0
    5002     .16       0  5277.7     .07       0  5353.2     .16       0
  5848.5     .07       0  6222.7    .035       0
Bank Sta=4998,5002
XS Rating Curve= 0 ,0
Exp/Cntr=0.3,0.1

Type RM Length L Ch R = 1 ,12306   ,154,154,154
BEGIN DESCRIPTION:
Elm 01 20 12305.81
END DESCRIPTION:
XS GIS Cut Line= 4
      1521294.19      6812956.08      1521124.91      6812643.55
      1521071.26      6812371.18      1520905.11      6811480.99
#Sta/Elev= 30
  4627.4 2011.17  4647.8 2011.06    4683 2011.29  4727.6 2009.45  4759.1 2009.96
  4795.8  2008.4  4818.6  2006.1  4830.4  2007.5  4950.2 2009.07  4982.8 2011.22
  4988.5  2011.1  4997.5 2005.91  4997.8 2005.41  5001.5 2005.91    5006 2009.65
  5090.4 2008.15  5108.7  2006.5  5259.5 2005.91  5699.7 2007.34  5711.3 2008.64
    5752 2007.46  5769.8 2008.17  5895.1 2008.63  5935.1 2008.66  5949.4 2007.39
  5955.4 2006.57  5985.9 2008.85  6118.2 2008.27  6148.7 2009.61    6166 2008.81
#Mann= 7 ,-1 , 0
  4627.4    .035       0  4647.8     .16       0  4997.5     .07       0
  5001.5     .16       0  5769.8     .07       0  5895.1     .16       0
  5949.4     .07       0
Bank Sta=4997.5,5001.5
XS Rating Curve= 0 ,0
Exp/Cntr=0.3,0.1