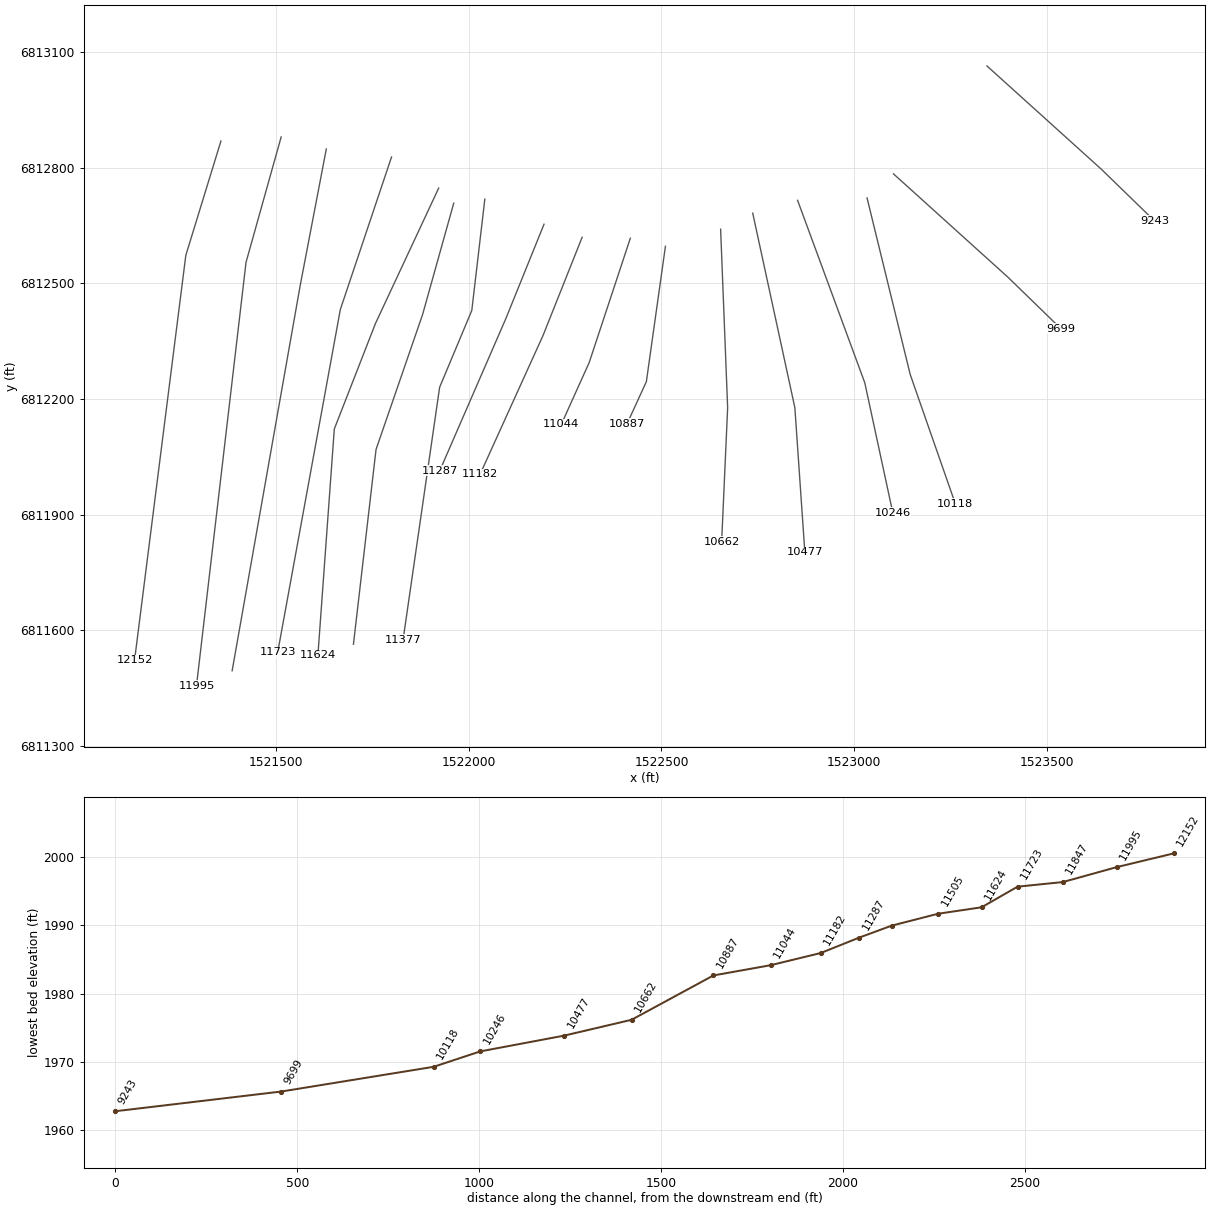
HEC-RAS study Elm 01 20.prj: Elm 01 20 Base Level Engineering

--- Elm 01 20.g01 (geometry) --- (continued)

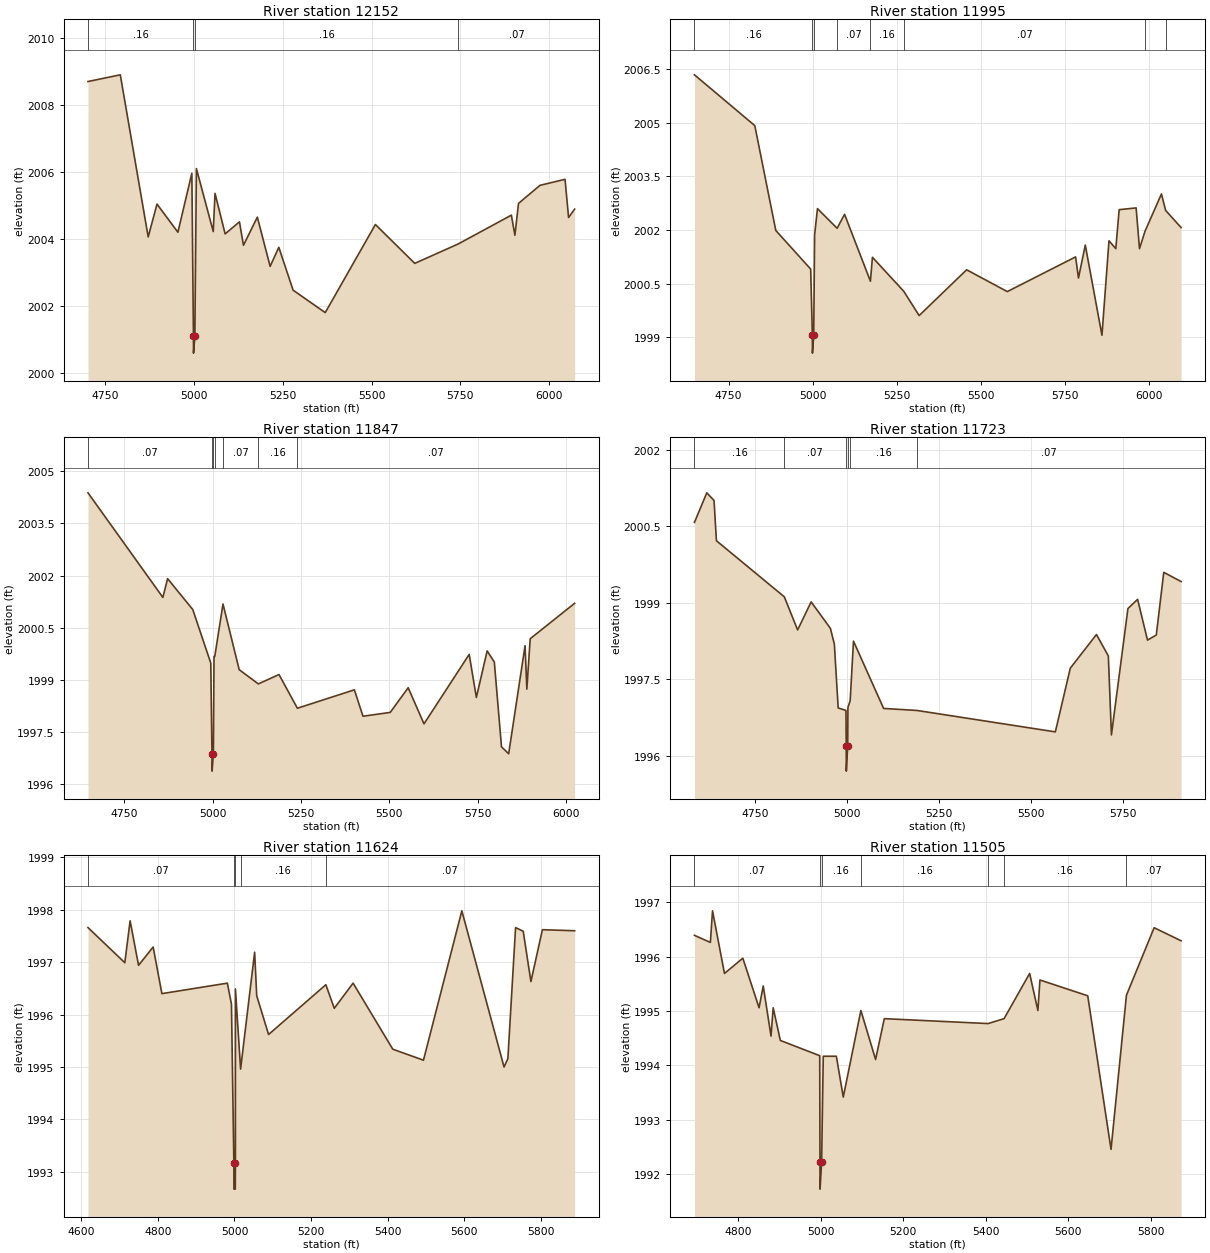
Type RM Length L Ch R = 1 ,12152   ,157,157,157
BEGIN DESCRIPTION:
Elm 01 20 12152.49
END DESCRIPTION:
XS GIS Cut Line= 3
      1521356.68      6812870.11      1521265.53      6812573.24
       1521132.4      6811521.18
#Sta/Elev= 30
  4700.9 2008.69  4791.9 2008.89  4870.5 2004.05  4895.3 2005.03  4954.2 2004.19
  4993.5 2005.95    4998 2001.08  4998.2 2000.58    5002 2001.08  5006.3 2006.09
  5053.8 2004.21  5058.8 2005.35  5087.3 2004.14  5127.6  2004.5  5138.9  2003.8
    5178 2004.64  5214.1 2003.17  5238.5 2003.74  5278.8 2002.46  5369.3 2001.79
  5510.6 2004.42  5621.5 2003.26  5744.1 2003.84  5893.7  2004.7  5903.7  2004.1
  5913.8 2005.05  5974.3 2005.59  6044.9 2005.77  6054.9 2004.63  6071.9 2004.88
#Mann= 4 ,-1 , 0
  4700.9     .16       0    4998     .07       0    5002     .16       0
  5744.1     .07       0
Bank Sta=4998,5002
XS Rating Curve= 0 ,0
Exp/Cntr=0.3,0.1

Type RM Length L Ch R = 1 ,11995   ,148,148,148
BEGIN DESCRIPTION:
Elm 01 20 11998.51
END DESCRIPTION:
XS GIS Cut Line= 3
      1521512.94      6812880.56      1521421.78      6812555.01
       1521293.2      6811455.38
#Sta/Elev= 30
  4648.9 2006.34  4828.1 2004.92  4890.4 2001.99    4994 2000.91  4999.1 1999.06
  4999.3 1998.56  5003.1 1999.06  5005.7 2001.86  5014.2  2002.6  5072.6 2002.05
  5094.7 2002.44  5171.5 2000.57  5177.4 2001.24  5270.4 2000.29  5316.2 1999.61
  5457.2 2000.89    5578 2000.28  5780.8 2001.25  5789.4 2000.66  5809.6 2001.58
  5859.1 1999.06    5880  2001.7  5900.2 2001.48  5910.2 2002.57  5960.6 2002.62
  5970.6 2001.48  5987.1 2001.97  6035.8 2003.01  6048.2 2002.55  6094.1 2002.07
#Mann= 8 ,-1 , 0
  4648.9     .16       0  4999.1     .07       0  5003.1     .16       0
  5072.6     .07       0  5171.5     .16       0  5270.4     .07       0
  5987.1    .035       0  6048.2     .07       0
Bank Sta=4999.1,5003.1
XS Rating Curve= 0 ,0
Exp/Cntr=0.3,0.1

Type RM Length L Ch R = 1 ,11847   ,124,124,124
BEGIN DESCRIPTION:
Elm 01 20 11846.5
END DESCRIPTION:
XS GIS Cut Line= 3
      1521630.11      6812849.27      1521562.41      6812495.11
      1521385.74      6811494.25
#Sta/Elev= 30
  4647.5 2004.38  4859.3 2001.37  4872.8 2001.91    4944 2001.02  4994.9 1999.48
  4998.3 1996.87  4998.6 1996.37  5002.3 1996.87  5004.1 1999.67  5006.2 1999.67
  5029.5 2001.18  5075.3 1999.29  5129.5 1998.88  5187.9 1999.15    5240 1998.18
  5401.2 1998.71  5425.6 1997.95  5502.7 1998.06  5553.5 1998.77  5598.2 1997.73
  5726.1 1999.73  5746.4 1998.49  5776.9 1999.83  5797.2 1999.51  5817.5 1997.07
  5837.8 1996.87  5884.2 1999.98  5889.2 1998.73  5898.7 2000.18  6024.4  2001.2
#Mann= 7 ,-1 , 0
  4647.5     .07       0  4998.3     .07       0  5002.3     .16       0
  5006.2     .16       0  5029.5     .07       0  5129.5     .16       0
    5240     .07       0
Bank Sta=4998.3,5002.3
XS Rating Curve= 0 ,0
Exp/Cntr=0.3,0.1

Type RM Length L Ch R = 1 ,11723   ,99,99,99
BEGIN DESCRIPTION:
Elm 01 20 11722.74
END DESCRIPTION:
XS GIS Cut Line= 3
      1521799.39      6812828.46      1521666.57      6812432.61
      1521503.89      6811541.68
#Sta/Elev= 30
  4585.7 2000.58  4619.2 2001.16  4638.9 2001.01  4645.4 2000.22    4830 1999.12
  4866.2 1998.47    4903 1999.02  4955.4  1998.5  4966.1 1998.19  4976.5 1996.94
  4997.6 1996.89  4998.4  1996.2  4998.6  1995.7  5002.4  1996.2    5003 1996.95
  5009.1 1997.08  5018.1 1998.25    5100 1996.93  5191.1 1996.89    5567 1996.47
  5607.7 1997.72  5678.8 1998.38  5711.1 1997.96  5719.5 1996.41  5764.4 1998.89
  5790.7 1999.07  5817.6 1998.27  5841.5 1998.37  5861.8  1999.6  5908.9 1999.42
#Mann= 6 ,-1 , 0
  4585.7     .16       0    4830     .07       0  4998.4     .07       0
  5002.4     .16       0  5009.1     .16       0  5191.1     .07       0
Bank Sta=4998.4,5002.4
XS Rating Curve= 0 ,0
Exp/Cntr=0.3,0.1

Type RM Length L Ch R = 1 ,11624   ,119,119,119
BEGIN DESCRIPTION:
Elm 01 20 11623.9
END DESCRIPTION:
XS GIS Cut Line= 4
      1521921.79      6812747.74      1521757.72      6812396.15
      1521650.89      6812122.12      1521608.28      6811534.06
#Sta/Elev= 30
  4617.3 1997.66  4713.5 1996.99  4727.4 1997.79  4749.4 1996.94  4787.6 1997.29
  4810.4  1996.4  4981.5  1996.6  4992.2  1996.2  4998.5 1993.17  4998.7 1992.67
  5002.2 1992.67  5002.5 1993.17  5002.6 1996.49  5016.1 1994.96  5052.8 1997.19
  5058.2 1996.36  5089.2 1995.62  5238.9 1996.57  5260.9 1996.12  5310.1  1996.6
  5413.8 1995.34    5494 1995.13  5594.3 1997.98  5704.6    1995  5714.6 1995.16
  5734.7 1997.66  5754.7 1997.59  5774.8 1996.63  5804.8 1997.62    5889  1997.6
#Mann= 5 ,-1 , 0
  4617.3     .07       0  4998.5     .07       0  5002.5     .16       0
  5016.1     .16       0  5238.9     .07       0
Bank Sta=4998.5,5002.5
XS Rating Curve= 0 ,0
Exp/Cntr=0.3,0.1

Type RM Length L Ch R = 1 ,11505   ,128,128,128
BEGIN DESCRIPTION:
Elm 01 20 11504.57
END DESCRIPTION:
XS GIS Cut Line= 4
      1521960.84      6812708.62      1521880.11      6812419.59
      1521759.22      6812069.01      1521700.55      6811563.13
#Sta/Elev= 30
  4693.7 1996.39  4732.3 1996.26  4737.5 1996.84  4766.5 1995.69    4811 1995.97
  4850.4 1995.06  4860.5 1995.46  4879.4 1994.54  4884.6 1995.06    4902 1994.46
  4997.5 1994.18  4998.1 1992.23  4998.3 1991.73  5002.1 1992.23  5006.1 1994.17
  5037.8 1994.17  5054.6 1993.42  5097.3 1995.01    5133 1994.11  5154.1 1994.86
  5405.8 1994.77  5444.6 1994.86  5506.6 1995.69  5526.6 1995.01  5531.6 1995.57
  5647.5 1995.28    5704 1992.46  5741.4 1995.29  5808.6 1996.53  5873.9 1996.29
#Mann= 7 ,-1 , 0
  4693.7     .07       0  4998.1     .07       0  5002.1     .16       0
  5097.3     .16       0  5405.8     .07       0  5444.6     .16       0
  5741.4     .07       0
Bank Sta=4998.1,5002.1
XS Rating Curve= 0 ,0
Exp/Cntr=0.3,0.1

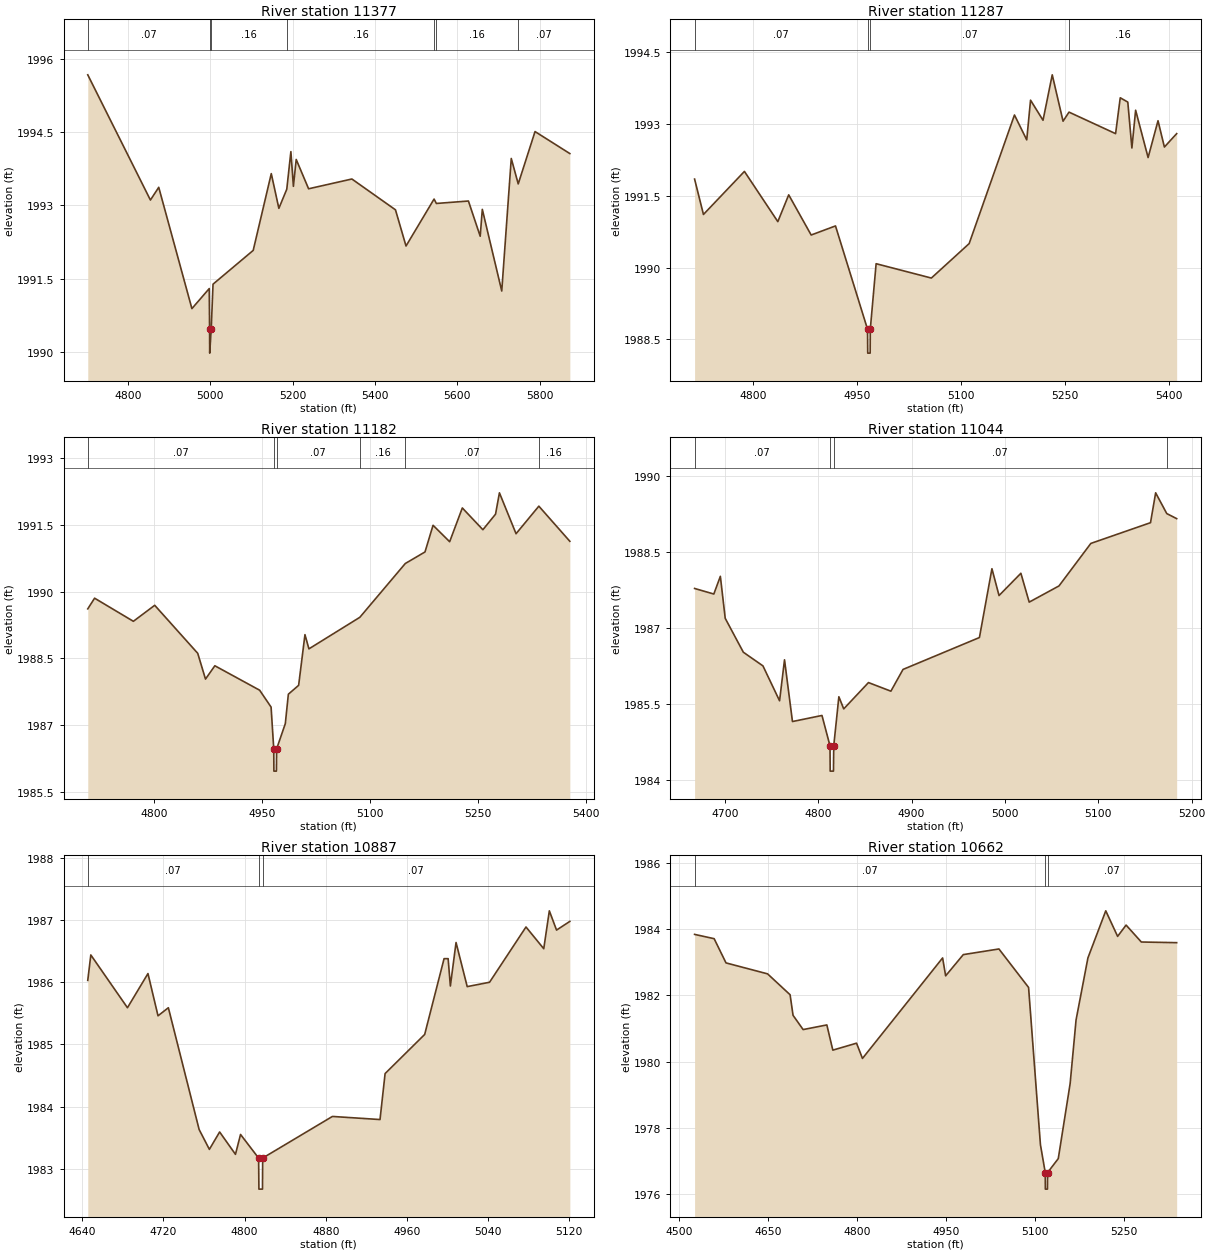
Type RM Length L Ch R = 1 ,11377   ,90,90,90
BEGIN DESCRIPTION:
Elm 01 20 11377.23
END DESCRIPTION:
XS GIS Cut Line= 4
      1522041.58      6812719.11      1522007.72      6812430.01
      1521924.27      6812230.48      1521829.32      6811574.37
#Sta/Elev= 30
  4702.6 1995.67  4854.7 1993.11  4874.9 1993.37  4955.4 1990.89  4997.5  1991.3
  4998.3 1990.48  4998.6 1989.98  5002.3 1990.48  5006.7 1991.39  5104.2 1992.08
  5148.1 1993.65  5166.5 1992.94  5185.7 1993.33  5195.7  1994.1  5201.8 1993.39
  5208.6 1993.94  5238.7 1993.34  5343.8 1993.54  5449.6 1992.91  5475.2 1992.17
  5543.3 1993.13  5548.9 1993.04  5626.7 1993.09  5655.3 1992.37  5660.4 1992.92
  5707.6 1991.25  5730.7 1993.96  5747.6 1993.44  5788.4 1994.51  5872.9 1994.06
#Mann= 7 ,-1 , 0
  4702.6     .07       0  4998.3     .07       0  5002.3     .16       0
  5185.7     .16       0  5543.3     .07       0  5548.9     .16       0
  5747.6     .07       0
Bank Sta=4998.3,5002.3
XS Rating Curve= 0 ,0
Exp/Cntr=0.3,0.1

Type RM Length L Ch R = 1 ,11287   ,105,105,105
BEGIN DESCRIPTION:
Elm 01 20 11287.39
END DESCRIPTION:
XS GIS Cut Line= 3
       1522195.2      6812653.93      1522096.26      6812409.17
       1521924.4      6812013.37
#Sta/Elev= 30
  4715.1 1991.85  4727.9 1991.11    4787 1992.01  4835.2 1990.96  4850.9 1991.52
  4883.3 1990.68  4918.4 1990.87  4964.6 1988.71  4964.9 1988.21  4968.4 1988.21
  4968.6 1988.71    4977 1990.08  5056.7 1989.78  5111.2  1990.5  5176.6 1993.19
  5194.3 1992.67  5199.8  1993.5  5217.8 1993.08  5231.1 1994.03  5246.7 1993.06
  5255.3 1993.25  5322.5  1992.8  5329.2 1993.55  5340.1 1993.46    5346  1992.5
  5351.4 1993.29  5369.4  1992.3  5383.7 1993.07  5392.9 1992.52  5410.6  1992.8
#Mann= 4 ,-1 , 0
  4715.1     .07       0  4964.6     .07       0  4968.6     .07       0
  5255.3     .16       0
Bank Sta=4964.6,4968.6
XS Rating Curve= 0 ,0
Exp/Cntr=0.3,0.1

Type RM Length L Ch R = 1 ,11182   ,138,138,138
BEGIN DESCRIPTION:
Elm 01 20 11181.64
END DESCRIPTION:
XS GIS Cut Line= 3
      1522294.17      6812620.11      1522192.61       6812364.9
      1522029.29      6812004.56
#Sta/Elev= 30
  4707.9 1989.61  4717.4 1989.85  4771.3 1989.33    4801 1989.69  4860.8 1988.61
  4871.6 1988.03  4884.6 1988.33  4946.9 1987.78  4962.8  1987.4  4966.5 1986.46
  4966.7 1985.96  4970.2 1985.96  4970.5 1986.46  4982.6 1987.03  4986.8 1987.69
  5001.1 1987.89  5009.9 1989.03  5015.4 1988.71  5086.2 1989.42  5149.4 1990.63
  5176.8 1990.89    5188 1991.49  5211.1 1991.12  5228.7 1991.88  5257.3 1991.39
  5274.9 1991.74  5280.3 1992.22  5303.4  1991.3  5335.1 1991.92  5378.2 1991.13
#Mann= 6 ,-1 , 0
  4707.9     .07       0  4966.5     .07       0  4970.5     .07       0
  5086.2     .16       0  5149.4     .07       0  5335.1     .16       0
Bank Sta=4966.5,4970.5
XS Rating Curve= 0 ,0
Exp/Cntr=0.3,0.1

Type RM Length L Ch R = 1 ,11044   ,157,157,157
BEGIN DESCRIPTION:
Elm 01 20 11043.93
END DESCRIPTION:
XS GIS Cut Line= 3
      1522419.19      6812617.54      1522312.41      6812294.59
      1522240.03       6812134.1
#Sta/Elev= 30
  4667.7 1987.78  4688.3 1987.67  4695.3 1988.02  4700.5 1987.19  4719.9 1986.52
  4740.9 1986.25  4758.7 1985.56    4764 1986.37  4772.5 1985.15  4804.1 1985.27
  4812.7 1984.67  4812.9 1984.17  4816.4 1984.17  4816.7 1984.67  4822.2 1985.64
  4827.4  1985.4  4853.9 1985.92  4877.9 1985.75  4890.9 1986.18  4972.7 1986.81
  4986.1 1988.17  4993.7 1987.64  5017.1 1988.08    5026 1987.51  5057.9 1987.83
    5092 1988.67  5155.9 1989.08  5161.4 1989.67  5173.3 1989.26  5183.9 1989.16
#Mann= 4 ,-1 , 0
  4667.7     .07       0  4812.7     .07       0  4816.7     .07       0
  5173.3     .16       0
Bank Sta=4812.7,4816.7
XS Rating Curve= 0 ,0
Exp/Cntr=0.3,0.1

Type RM Length L Ch R = 1 ,10887   ,225,225,225
BEGIN DESCRIPTION:
Elm 01 20 10887.3
END DESCRIPTION:
XS GIS Cut Line= 3
      1522510.32      6812596.67      1522460.84      6812245.11
      1522410.94      6812136.12
#Sta/Elev= 30
  4645.6 1986.03  4648.6 1986.44  4684.7 1985.59  4704.9 1986.14  4714.8 1985.46
    4725 1985.59  4755.3 1983.63  4765.4 1983.31  4775.5 1983.59  4791.1 1983.23
  4796.1 1983.55  4813.9 1983.17  4814.2 1982.67  4817.7 1982.67  4817.9 1983.17
  4886.6 1983.84  4933.5 1983.79  4938.5 1984.53  4977.5 1985.16  4996.6 1986.38
  5000.6 1986.38  5002.8 1985.94  5008.4 1986.64  5019.4 1985.93  5041.4    1986
  5077.3 1986.89  5094.8 1986.54  5100.3 1987.15  5107.4 1986.84  5120.5 1986.98
#Mann= 3 ,-1 , 0
  4645.6     .07       0  4813.9     .07       0  4817.9     .07       0
Bank Sta=4813.9,4817.9
XS Rating Curve= 0 ,0
Exp/Cntr=0.3,0.1

Type RM Length L Ch R = 1 ,10662   ,185,185,185
BEGIN DESCRIPTION:
Elm 01 20 10662.21
END DESCRIPTION:
XS GIS Cut Line= 3
      1522653.55      6812640.97      1522671.78       6812177.4
      1522656.16      6811828.48
#Sta/Elev= 30
  4525.5 1983.84  4558.5 1983.71  4578.5 1982.98  4648.6 1982.65  4686.6 1982.02
  4691.6  1981.4  4708.6 1980.97  4748.6 1981.11  4758.7 1980.35  4798.7 1980.56
  4808.7  1980.1  4943.9 1983.13    4949 1982.59  4978.8 1983.23  5038.9  1983.4
  5088.9 1982.24  5108.9  1977.5    5117 1976.66  5117.2 1976.16  5120.7 1976.16
    5121 1976.66    5139 1977.08    5159 1979.34    5169 1981.26    5189 1983.13
  5219.1 1984.55  5239.1 1983.78  5253.4 1984.12  5279.1 1983.61  5338.7 1983.59
#Mann= 3 ,-1 , 0
  4525.5     .07       0    5117     .07       0    5121     .07       0
Bank Sta=5117,5121
XS Rating Curve= 0 ,0
Exp/Cntr=0.3,0.1

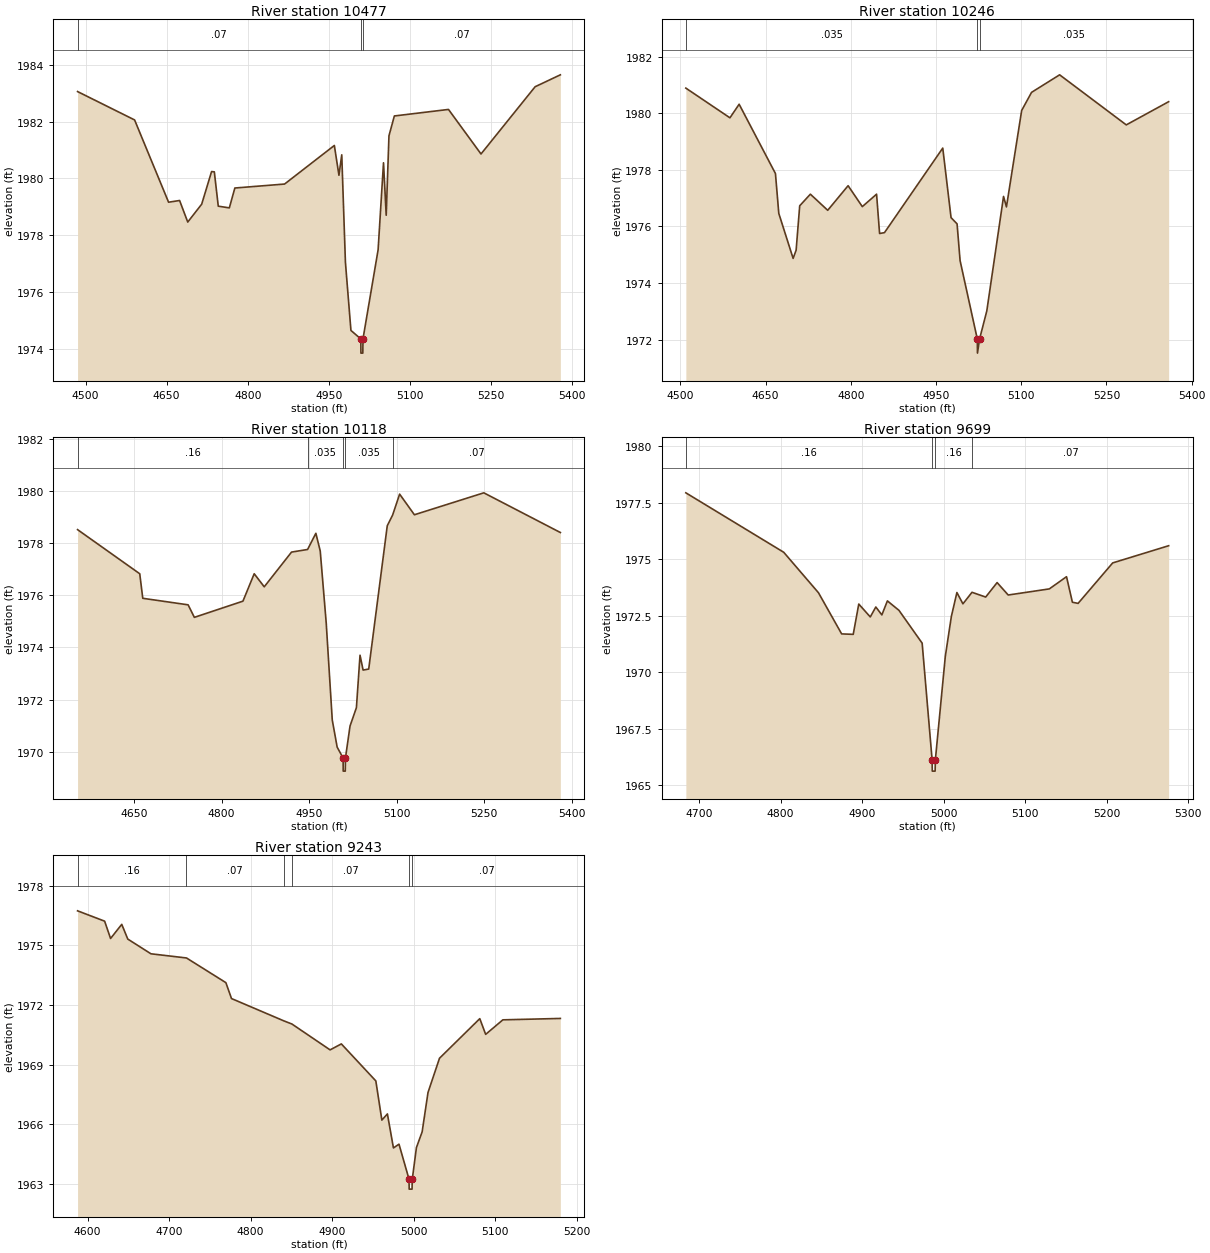
Type RM Length L Ch R = 1 ,10477   ,231,231,231
BEGIN DESCRIPTION:
Elm 01 20 10477.28
END DESCRIPTION:
XS GIS Cut Line= 3
      1522736.88      6812682.64      1522846.26       6812177.4
      1522872.19      6811801.44
#Sta/Elev= 30
    4485 1983.06  4590.6 1982.06  4653.5 1979.16  4673.9 1979.22    4689 1978.46
  4714.8 1979.09  4733.1 1980.24  4738.2 1980.23  4745.5 1979.02    4766 1978.96
  4776.2 1979.66  4868.3  1979.8  4960.4 1981.16  4968.9 1980.11  4974.1 1980.83
  4980.9 1977.04  4991.1 1974.64  5009.4 1974.34  5009.6 1973.84  5013.1 1973.84
  5013.4 1974.34  5041.4 1977.48  5051.4 1980.55  5056.4  1978.7  5061.5  1981.5
  5071.5  1982.2  5171.7 1982.43  5231.9 1980.86  5332.1 1983.23  5378.8 1983.65
#Mann= 3 ,-1 , 0
    4485     .07       0  5009.4     .07       0  5013.4     .07       0
Bank Sta=5009.4,5013.4
XS Rating Curve= 0 ,0
Exp/Cntr=0.3,0.1

Type RM Length L Ch R = 1 ,10246   ,128,128,128
BEGIN DESCRIPTION:
Elm 01 20 10281.89
END DESCRIPTION:
XS GIS Cut Line= 3
      1522853.28      6812716.03      1523027.76      6812242.05
      1523100.35      6811905.06
#Sta/Elev= 30
  4509.7 1980.89  4587.3 1979.84  4603.5 1980.32  4667.4 1977.87  4673.3 1976.46
  4698.5 1974.87  4703.8 1975.16  4710.1 1976.73  4728.9 1977.14  4759.4 1976.57
  4795.3 1977.44  4820.3  1976.7  4845.4 1977.14  4850.7 1975.75  4859.3 1975.78
  4961.9 1978.77  4976.5 1976.31  4987.1 1976.09  4992.4 1974.79  5022.7 1972.02
    5023 1971.52  5026.7 1972.02  5039.4 1973.01  5068.9 1977.06    5074 1976.69
  5100.8  1980.1  5118.2 1980.74  5167.6 1981.36  5284.9 1979.59  5359.5 1980.41
#Mann= 3 ,-1 , 0
  4509.7    .035       0  5022.7    .035       0  5026.7    .035       0
Bank Sta=5022.7,5026.7
XS Rating Curve= 0 ,0
Exp/Cntr=0.3,0.1

Type RM Length L Ch R = 1 ,10118   ,419,419,419
BEGIN DESCRIPTION:
Elm 01 20 10075.51
END DESCRIPTION:
XS GIS Cut Line= 3
      1523033.61      6812722.13      1523145.59       6812263.8
      1523262.77      6811927.87
#Sta/Elev= 30
  4553.2 1978.51  4659.8 1976.82    4665 1975.88  4742.7 1975.63  4753.4 1975.15
  4836.7 1975.77    4856 1976.82  4873.2 1976.32    4920 1977.65  4947.5 1977.75
  4961.7 1978.37  4969.2 1977.69  4979.5 1974.92  4989.8 1971.22  4998.2 1970.18
  5008.4 1969.76  5008.6 1969.26  5012.1 1969.26  5012.4 1969.76  5020.3 1970.99
  5031.2 1971.69  5037.4  1973.7  5042.7 1973.13  5052.3 1973.17  5084.1 1978.66
  5093.3 1979.07  5105.3 1979.87  5130.6 1979.08  5249.6 1979.92  5380.8  1978.4
#Mann= 5 ,-1 , 0
  4553.2     .16       0  4947.5    .035       0  5008.4    .035       0
  5012.4    .035       0  5093.3     .07       0
Bank Sta=5008.4,5012.4
XS Rating Curve= 0 ,0
Exp/Cntr=0.3,0.1

Type RM Length L Ch R = 1 ,9699    ,456,456,456
BEGIN DESCRIPTION:
Elm 01 20 5.0
END DESCRIPTION:
XS GIS Cut Line= 3
      1523102.27      6812784.68      1523399.13      6812516.46
      1523536.66      6812382.75
#Sta/Elev= 30
  4683.9 1977.94  4803.9 1975.31  4846.5 1973.52  4874.9  1971.7  4889.1 1971.68
  4895.9 1973.02    4910 1972.45  4916.8 1972.89  4924.2 1972.54    4931 1973.16
  4945.2 1972.74  4973.6 1971.29  4985.8 1966.13    4986 1965.63  4989.5 1965.63
  4989.8 1966.13    5002 1970.71  5009.4 1972.47  5016.2 1973.53  5023.6 1973.03
  5034.7 1973.54  5051.5 1973.33  5065.5 1973.97  5079.1 1973.42  5129.5 1973.69
  5150.6 1974.23  5157.8  1973.1  5164.8 1973.05  5207.2 1974.84  5275.8  1975.6
#Mann= 4 ,-1 , 0
  4683.9     .16       0  4985.8     .07       0  4989.8     .16       0
  5034.7     .07       0
Bank Sta=4985.8,4989.8
XS Rating Curve= 0 ,0
Exp/Cntr=0.3,0.1

Type RM Length L Ch R = 1 ,9243    ,222,222,222
BEGIN DESCRIPTION:
Elm 01 20 9242.61
END DESCRIPTION:
XS GIS Cut Line= 3
      1523344.93       6813064.9      1523641.81      6812796.66
      1523779.46      6812662.83
#Sta/Elev= 30
  4587.7 1976.73  4620.9 1976.21  4628.2 1975.34  4641.9 1976.05  4649.3 1975.31
  4677.7 1974.57  4721.3 1974.36  4769.6 1973.12  4776.5 1972.32  4840.6  1971.2
  4850.6 1971.04  4897.4 1969.74  4911.2 1970.04  4953.5 1968.18  4960.9 1966.21
  4967.7 1966.52  4975.1 1964.81  4981.9    1965  4994.2 1963.24  4994.4 1962.74
  4997.9 1962.74  4998.2 1963.24  5003.3 1964.83  5010.3 1965.62  5017.5  1967.6
  5031.6 1969.32    5081 1971.31  5088.2 1970.52  5109.3 1971.25  5179.8 1971.32
#Mann= 6 ,-1 , 0
  4587.7     .16       0  4721.3     .07       0  4840.6     .16       0
  4850.6     .07       0  4994.2     .07       0  4998.2     .07       0
Bank Sta=4994.2,4998.2
XS Rating Curve= 0 ,0
Exp/Cntr=0.3,0.1