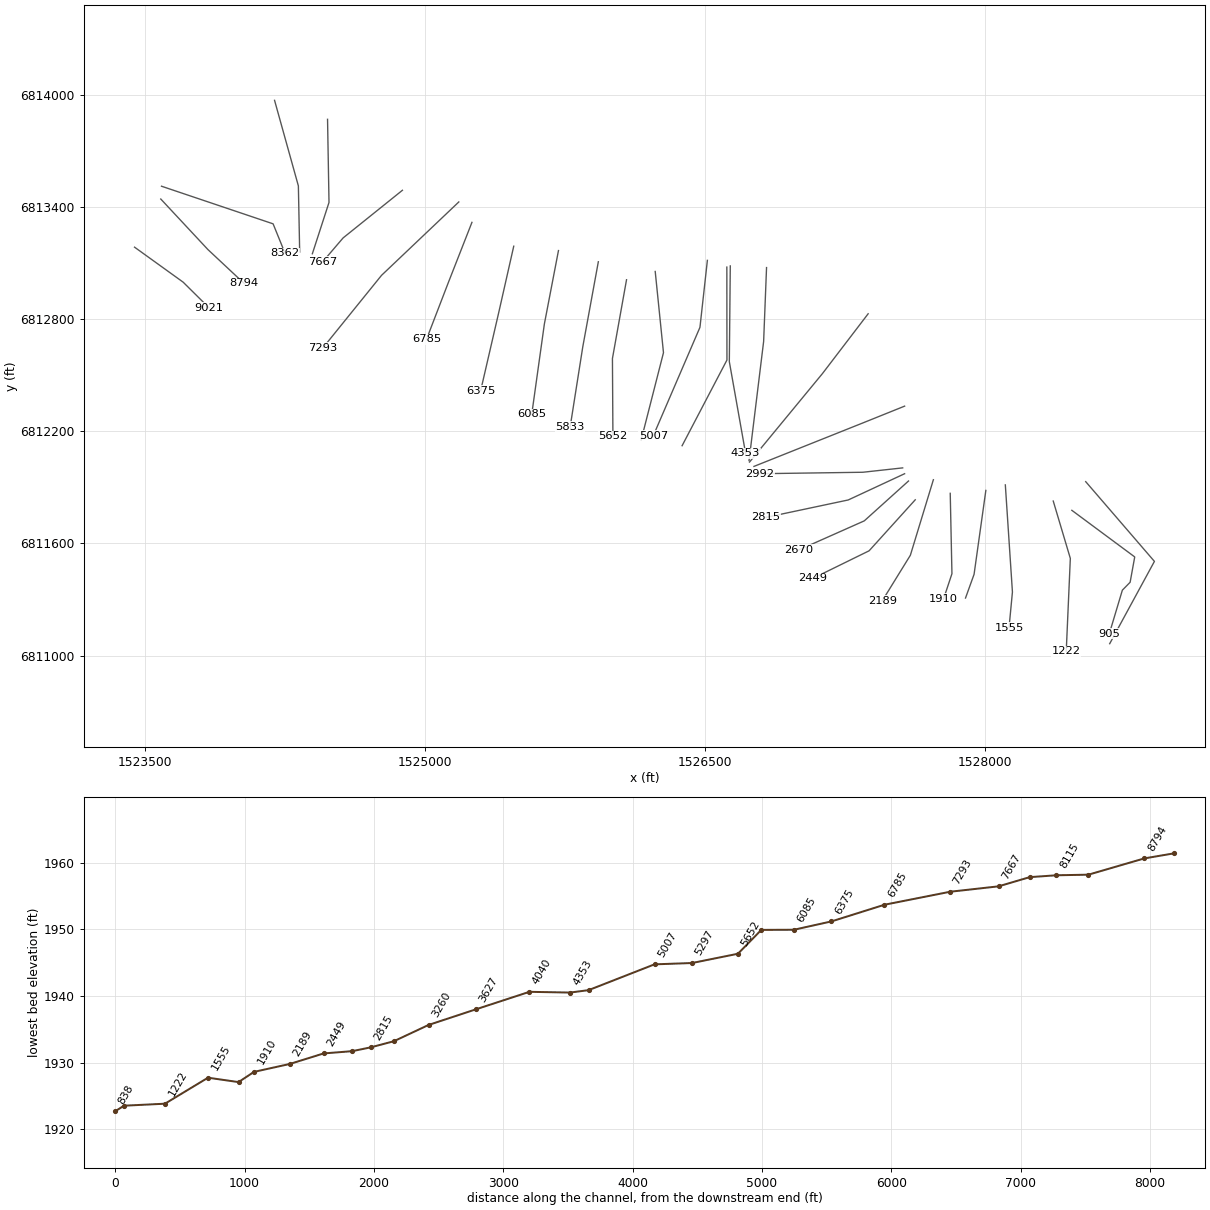
HEC-RAS study Elm 01 20.prj: Elm 01 20 Base Level Engineering

--- Elm 01 20.g01 (geometry) --- (continued)

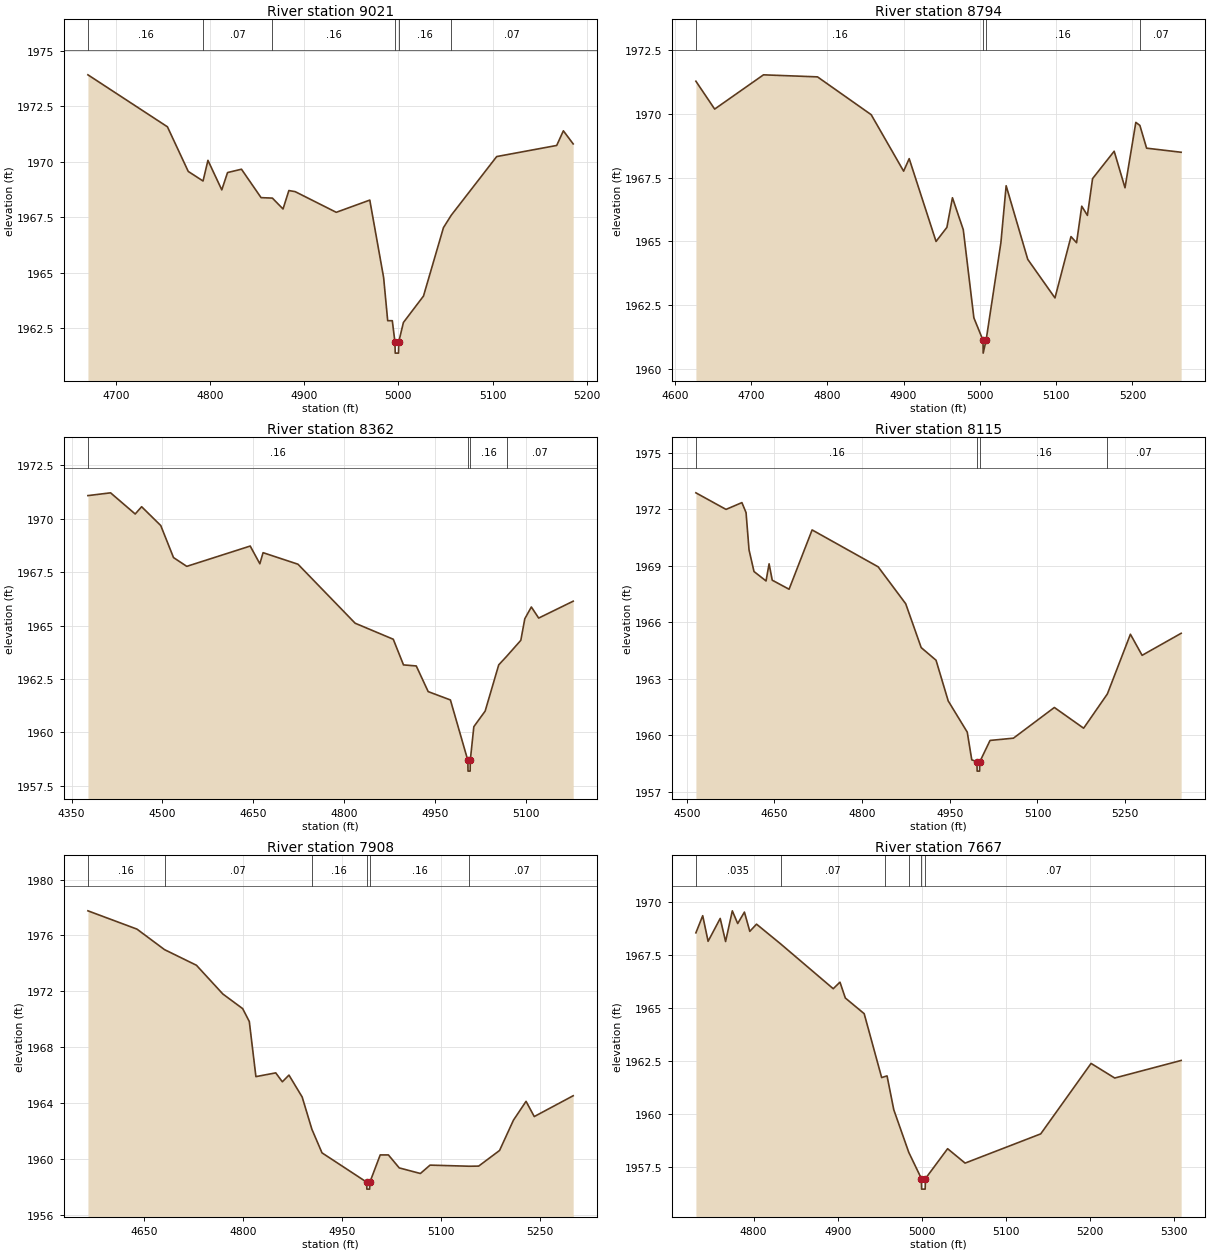
Type RM Length L Ch R = 1 ,9021    ,227,227,227
BEGIN DESCRIPTION:
Elm 01 20 9020.22
END DESCRIPTION:
XS GIS Cut Line= 3
      1523446.48       6813187.3      1523706.92      6812999.79
      1523844.82      6812863.08
#Sta/Elev= 30
  4670.5 1973.91  4754.9 1971.57    4777 1969.56  4792.7 1969.13  4797.9 1970.06
  4812.6 1968.73  4818.7 1969.51  4833.5 1969.66  4854.3 1968.38  4866.3 1968.36
  4877.6 1967.87  4883.8  1968.7  4890.5 1968.65  4934.1 1967.72  4969.7 1968.27
  4984.4 1964.78  4988.7 1962.84  4993.6 1962.84  4996.4 1961.88  4996.7 1961.38
  5000.2 1961.38  5000.4 1961.88  5005.4 1962.76  5026.7 1963.95  5047.9 1967.03
  5056.2 1967.59  5104.4 1970.23  5168.1 1970.73  5175.2 1971.39  5185.6  1970.8
#Mann= 6 ,-1 , 0
  4670.5     .16       0  4792.7     .07       0  4866.3     .16       0
  4996.4     .07       0  5000.4     .16       0  5056.2     .07       0
Bank Sta=4996.4,5000.4
XS Rating Curve= 0 ,0
Exp/Cntr=0.3,0.1

Type RM Length L Ch R = 1 ,8794    ,432,432,432
BEGIN DESCRIPTION:
Elm 01 20 8794
END DESCRIPTION:
XS GIS Cut Line= 3
      1523587.09      6813445.13      1523839.73      6813174.27
      1524033.75      6812992.74
#Sta/Elev= 30
  4627.8 1971.27  4652.4 1970.18  4716.4 1971.52  4787.2 1971.44  4857.6 1969.96
  4900.1 1967.75  4907.4 1968.24  4942.6    1965  4956.8 1965.55  4964.1 1966.71
  4978.3 1965.46  4992.2 1962.01  5004.2 1961.13  5004.4 1960.63  5008.2 1961.13
  5027.6 1964.95  5034.5 1967.18  5062.8  1964.3  5098.5 1962.79  5119.5 1965.19
  5126.8 1964.95  5133.6 1966.38    5141 1966.02  5147.8 1967.46  5176.1 1968.53
  5190.3  1967.1  5204.5 1969.66  5209.8 1969.54  5218.6 1968.65  5263.9 1968.49
#Mann= 4 ,-1 , 0
  4627.8     .16       0  5004.2     .07       0  5008.2     .16       0
  5209.8     .07       0
Bank Sta=5004.2,5008.2
XS Rating Curve= 0 ,0
Exp/Cntr=0.3,0.1

Type RM Length L Ch R = 1 ,8362    ,247,247,247
BEGIN DESCRIPTION:
Elm 01 20 8359.7
END DESCRIPTION:
XS GIS Cut Line= 3
      1523590.97      6813513.73      1524188.69      6813312.29
      1524252.98        6813154.
#Sta/Elev= 30
  4377.1 1971.08  4414.5 1971.21  4455.2 1970.22  4465.8 1970.56  4497.4 1969.68
  4518.5 1968.18  4540.4 1967.77  4645.2 1968.72  4661.1 1967.89  4666.4 1968.41
  4724.1 1967.87  4818.5 1965.11  4881.5 1964.36  4898.4 1963.16  4919.5 1963.11
  4939.2 1961.91  4975.9 1961.52  5004.7 1958.69    5005 1958.19  5008.5 1958.19
  5008.7 1958.69  5014.6 1960.27  5033.3    1961  5055.7 1963.16  5069.1 1963.57
  5092.2 1964.31  5098.8 1965.32  5109.6 1965.87  5121.7 1965.35  5178.7 1966.14
#Mann= 4 ,-1 , 0
  4377.1     .16       0  5004.7     .07       0  5008.7     .16       0
  5069.1     .07       0
Bank Sta=5004.7,5008.7
XS Rating Curve= 0 ,0
Exp/Cntr=0.3,0.1

Type RM Length L Ch R = 1 ,8115    ,207,207,207
BEGIN DESCRIPTION:
Elm 01 20 8115.16
END DESCRIPTION:
XS GIS Cut Line= 3
      1524196.49      6813973.79       1524324.1      6813515.41
      1524331.09      6813161.19
#Sta/Elev= 30
  4515.7 1972.88  4567.2    1972  4594.4 1972.36  4601.5 1971.83  4606.6 1969.85
  4615.1  1968.7  4635.7  1968.2  4640.9 1969.11  4646.3 1968.24  4675.1 1967.76
  4714.5 1970.91  4827.5 1968.95  4874.6 1966.99  4901.1 1964.66  4926.5 1963.99
  4947.3 1961.83  4979.9 1960.17  4987.6  1958.7  4996.5  1958.6  4996.8  1958.1
    5001  1958.1  5001.4  1958.6  5018.9 1959.73  5058.9 1959.85  5128.9 1961.48
    5179 1960.38  5219.6  1962.2    5259 1965.37    5279 1964.25  5345.8 1965.42
#Mann= 4 ,-1 , 0
  4515.7     .16       0  4996.5     .07       0  5001.4     .16       0
  5219.6     .07       0
Bank Sta=4996.5,5001.4
XS Rating Curve= 0 ,0
Exp/Cntr=0.3,0.1

Type RM Length L Ch R = 1 ,7908    ,241,241,241
BEGIN DESCRIPTION:
Elm 01 20 7908.11
END DESCRIPTION:
XS GIS Cut Line= 3
      1524480.36      6813872.14      1524488.17      6813426.87
        1524399.      6813152.01
#Sta/Elev= 30
  4565.5 1977.76  4639.7 1976.45  4681.4 1974.98  4729.7 1973.86  4769.7  1971.8
  4799.7 1970.75  4809.7 1969.83  4819.7 1965.88  4849.7 1966.15  4859.7 1965.51
  4869.7 1965.99  4889.7 1964.42  4904.4 1962.11  4919.7 1960.42  4987.3 1958.32
  4987.6 1957.82  4991.8 1957.82  4992.2 1958.32  5007.8 1960.27  5020.2 1960.27
  5036.6 1959.34  5068.6 1958.94  5083.2 1959.54  5142.9 1959.46  5156.8 1959.47
  5188.4 1960.59  5209.4 1962.76  5228.5 1964.11  5240.9 1963.02  5299.8 1964.51
#Mann= 6 ,-1 , 0
  4565.5     .16       0  4681.4     .07       0  4904.4     .16       0
  4987.3     .07       0  4992.2     .16       0  5142.9     .07       0
Bank Sta=4987.3,4992.2
XS Rating Curve= 0 ,0
Exp/Cntr=0.3,0.1

Type RM Length L Ch R = 1 ,7667    ,374,374,374
BEGIN DESCRIPTION:
Elm 01 20 7666.75
END DESCRIPTION:
XS GIS Cut Line= 3
      1524881.41      6813491.99      1524563.69      6813236.77
      1524453.52        6813108.
#Sta/Elev= 30
  4731.4 1968.55  4739.5 1969.36  4745.9 1968.15  4760.3 1969.23  4766.7 1968.14
  4774.7 1969.59  4781.1 1968.99  4789.1 1969.53  4795.5 1968.62  4803.5 1968.96
  4832.1 1968.03  4894.7 1965.91  4902.7 1966.22  4909.1 1965.47  4931.5 1964.73
  4952.3 1961.71  4956.2 1961.76  4958.7 1961.79  4966.7 1960.19  4984.5 1958.18
  4999.5 1956.94  4999.8 1956.44    5004 1956.44  5004.4 1956.94  5030.7 1958.35
  5051.5 1957.67  5141.4 1959.05  5201.3 1962.38  5229.4 1961.69  5308.4 1962.52
#Mann= 6 ,-1 , 0
  4731.4    .035       0  4832.1     .07       0  4956.2     .16       0
  4984.5     .07       0  4999.5     .07       0  5004.4     .07       0
Bank Sta=4999.5,5004.4
XS Rating Curve= 0 ,0
Exp/Cntr=0.3,0.1

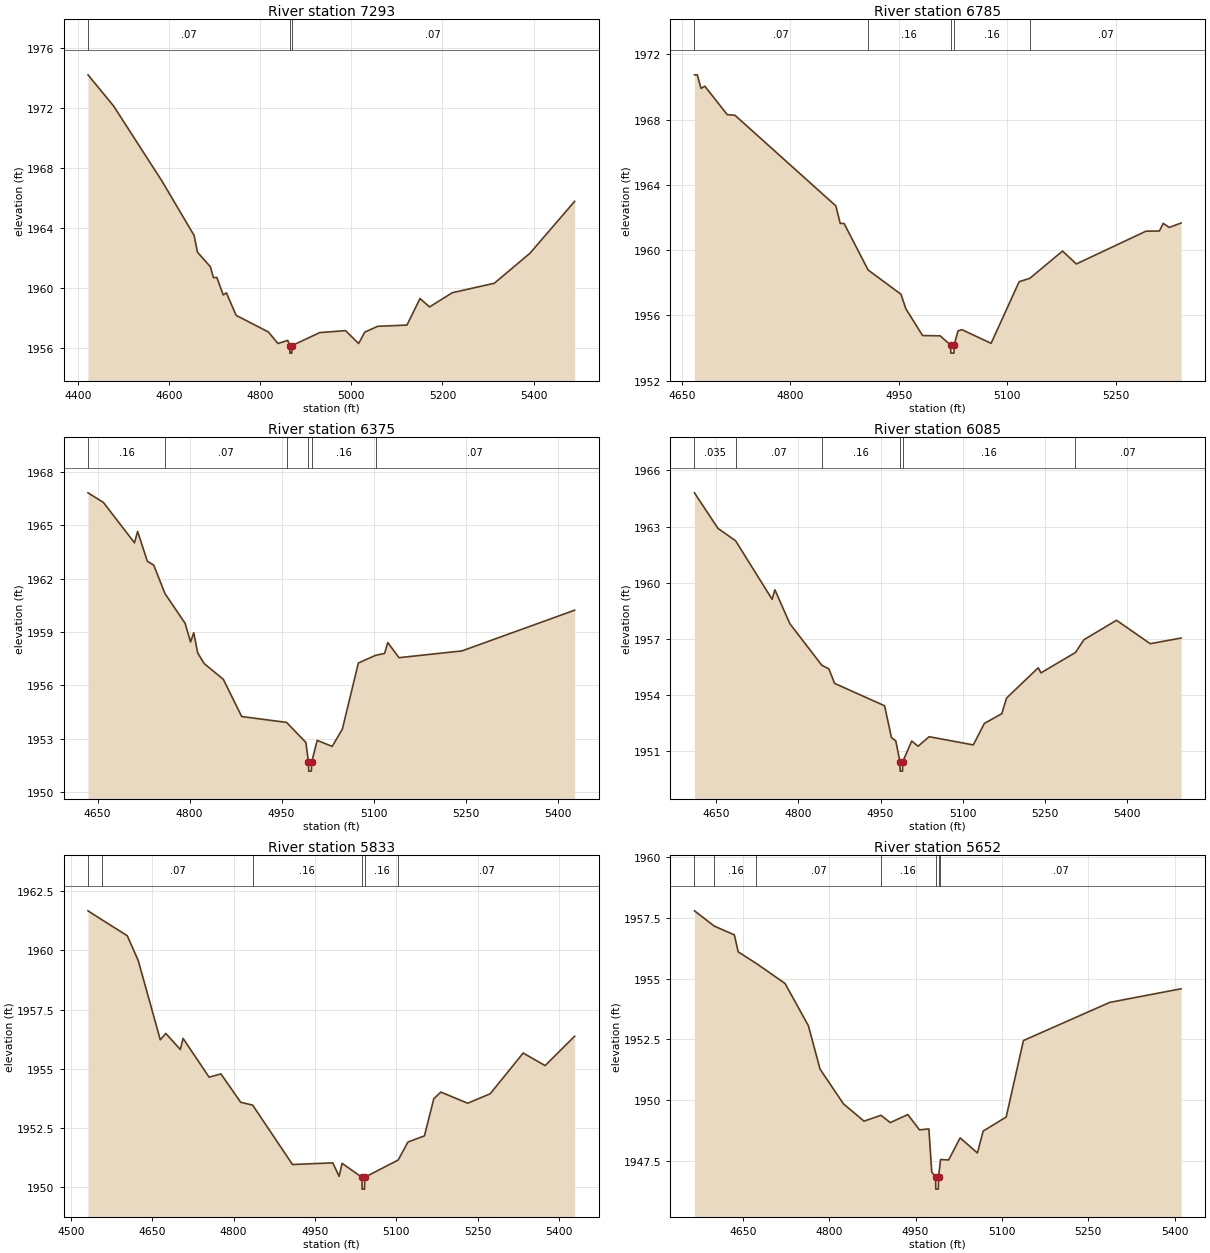
Type RM Length L Ch R = 1 ,7293    ,508,508,508
BEGIN DESCRIPTION:
Elm 01 20 7287.92
END DESCRIPTION:
XS GIS Cut Line= 3
      1525183.49      6813429.48      1524769.42      6813036.25
       1524456.4      6812649.09
#Sta/Elev= 30
  4421.4 1974.19  4477.9  1972.1  4584.2 1967.09  4654.6 1963.47  4661.9 1962.36
  4690.2 1961.39  4697.1 1960.66  4704.4 1960.68  4718.5 1959.51  4725.4 1959.65
  4746.8 1958.15  4817.6 1957.04  4838.7 1956.27  4860.1 1956.48  4864.5 1956.13
  4864.9 1955.63  4869.1 1955.63  4869.4 1956.13  4930.5    1957  4987.1 1957.13
  5015.9 1956.27  5029.3 1957.03    5058 1957.42    5122  1957.5  5150.7 1959.27
  5171.6 1958.71  5221.7 1959.66  5313.9 1960.29  5392.2 1962.29  5490.3 1965.75
#Mann= 3 ,-1 , 0
  4421.4     .07       0  4864.5     .07       0  4869.4     .07       0
Bank Sta=4864.5,4869.4
XS Rating Curve= 0 ,0
Exp/Cntr=0.3,0.1

Type RM Length L Ch R = 1 ,6785    ,410,410,410
BEGIN DESCRIPTION:
Elm 01 20 6785.16
END DESCRIPTION:
XS GIS Cut Line= 3
      1525253.81      6813320.15      1525126.19      6812994.58
      1525010.09      6812692.72
#Sta/Elev= 30
  4667.4 1970.75  4671.3 1970.75  4676.5 1969.92  4681.8 1970.05  4712.7 1968.31
  4723.4 1968.27    4863 1962.71    4869 1961.64  4874.4 1961.63  4907.6 1958.78
  4953.1 1957.29  4959.7 1956.41  4982.9 1954.76  5007.3 1954.74  5021.6 1954.18
    5022 1953.68  5026.3 1953.68  5026.6 1954.18  5031.9 1955.04  5037.3 1955.12
  5077.7 1954.28  5116.5 1958.06  5131.3 1958.27  5176.5 1959.94  5195.6 1959.15
    5292 1961.16  5310.5 1961.17  5315.8 1961.64  5324.1 1961.39  5340.5 1961.66
#Mann= 5 ,-1 , 0
  4667.4     .07       0  4907.6     .16       0  5021.6     .07       0
  5026.6     .16       0  5131.3     .07       0
Bank Sta=5021.6,5026.6
XS Rating Curve= 0 ,0
Exp/Cntr=0.3,0.1

Type RM Length L Ch R = 1 ,6375    ,290,290,290
BEGIN DESCRIPTION:
Elm 01 20 6374.55
END DESCRIPTION:
XS GIS Cut Line= 3
      1525477.74      6813192.45      1525397.02      6812835.73
      1525300.67      6812419.07
#Sta/Elev= 30
  4634.5 1966.83  4659.6 1966.29  4710.3 1964.02  4715.4 1964.66  4731.3 1962.98
  4741.6 1962.77  4760.1 1961.16  4792.9 1959.49  4801.7 1958.44  4806.9 1958.96
  4813.4 1957.83  4823.6 1957.24  4855.2 1956.34  4885.1 1954.25  4958.3 1953.92
  4989.8 1952.79    4994 1951.68  4994.4 1951.18  4998.7 1951.18  4999.1 1951.68
  5008.2 1952.91  5032.6 1952.57  5049.2 1953.54  5075.3 1957.26  5103.3 1957.69
  5118.1  1957.8  5123.2 1958.41  5141.6 1957.56  5244.2 1957.94  5427.9 1960.23
#Mann= 6 ,-1 , 0
  4634.5     .16       0  4760.1     .07       0  4958.3     .16       0
    4994     .07       0  4999.1     .16       0  5103.3     .07       0
Bank Sta=4994,4999.1
XS Rating Curve= 0 ,0
Exp/Cntr=0.3,0.1

Type RM Length L Ch R = 1 ,6085    ,252,252,252
BEGIN DESCRIPTION:
Elm 01 20 6085.31
END DESCRIPTION:
XS GIS Cut Line= 3
      1525717.34      6813169.09      1525641.81      6812775.83
      1525574.21      6812292.18
#Sta/Elev= 30
  4610.2  1964.8  4653.1  1962.9  4685.3 1962.24    4752 1959.11  4757.1 1959.62
  4784.4 1957.81  4842.7 1955.59  4855.7 1955.39  4866.1 1954.62  4957.5 1953.42
    4970 1951.72  4977.9 1951.55  4985.5 1950.43  4985.9 1949.93  4990.2 1949.93
  4990.6 1950.43    5007 1951.54  5018.6 1951.26  5038.8 1951.77  5119.5 1951.33
  5139.7 1952.48  5171.6    1953  5180.1 1953.83    5238 1955.45  5243.1 1955.18
  5306.1 1956.27  5321.5 1956.95    5381 1957.99  5442.6 1956.74    5499 1957.04
#Mann= 6 ,-1 , 0
  4610.2    .035       0  4685.3     .07       0  4842.7     .16       0
  4985.5     .07       0  4990.6     .16       0  5306.1     .07       0
Bank Sta=4985.5,4990.6
XS Rating Curve= 0 ,0
Exp/Cntr=0.3,0.1

Type RM Length L Ch R = 1 ,5833    ,181,181,181
BEGIN DESCRIPTION:
Elm 01 20 5832.84
END DESCRIPTION:
XS GIS Cut Line= 3
      1525930.88      6813109.18      1525847.54      6812653.43
      1525779.91      6812224.23
#Sta/Elev= 30
  4531.3 1961.67  4557.9 1961.28  4603.7 1960.62    4624 1959.57  4664.7 1956.22
  4674.8 1956.49  4701.6 1955.81  4706.7 1956.28  4754.8 1954.64  4776.5 1954.78
  4813.1 1953.58  4835.1 1953.46  4908.6 1950.95  4982.9 1951.02  4994.6 1950.45
  5000.1    1951  5036.7 1950.41  5037.1 1949.91  5041.4 1949.91  5041.8 1950.41
  5103.6 1951.14  5121.6  1951.9    5152 1952.16  5169.3 1953.73  5182.3 1954.01
  5231.8 1953.54  5273.4 1953.94  5334.2 1955.66  5374.7 1955.13  5429.1 1956.37
#Mann= 6 ,-1 , 0
  4531.3     .16       0  4557.9     .07       0  4835.1     .16       0
  5036.7     .07       0  5041.8     .16       0  5103.6     .07       0
Bank Sta=5036.7,5041.8
XS Rating Curve= 0 ,0
Exp/Cntr=0.3,0.1

Type RM Length L Ch R = 1 ,5652    ,355,355,355
BEGIN DESCRIPTION:
Elm 01 20 5651.5
END DESCRIPTION:
XS GIS Cut Line= 3
      1526081.92      6813012.82       1526006.4      6812590.93
        1526009.      6812174.24
#Sta/Elev= 30
  4565.9 1957.79  4600.4 1957.16  4635.2  1956.8  4641.9  1956.1  4673.6 1955.62
  4723.2  1954.8  4763.8 1953.06  4784.1 1951.27  4824.8 1949.84  4860.4 1949.13
  4889.9 1949.37    4906 1949.07  4936.5  1949.4  4956.8 1948.77  4973.1 1948.81
  4978.1 1947.03  4984.7 1946.83  4985.1 1946.33  4989.5 1946.33  4989.9 1946.83
  4991.7  1947.2  4993.4 1947.55  5007.4 1947.53  5027.4 1948.44  5057.4 1947.82
  5067.4 1948.72  5107.4  1949.3  5137.4 1952.45  5287.4 1954.02  5411.2 1954.58
#Mann= 7 ,-1 , 0
  4565.9     .07       0  4600.4     .16       0  4673.6     .07       0
  4889.9     .16       0  4984.7     .07       0  4989.9     .16       0
  4991.7     .07       0
Bank Sta=4984.7,4989.9
XS Rating Curve= 0 ,0
Exp/Cntr=0.3,0.1

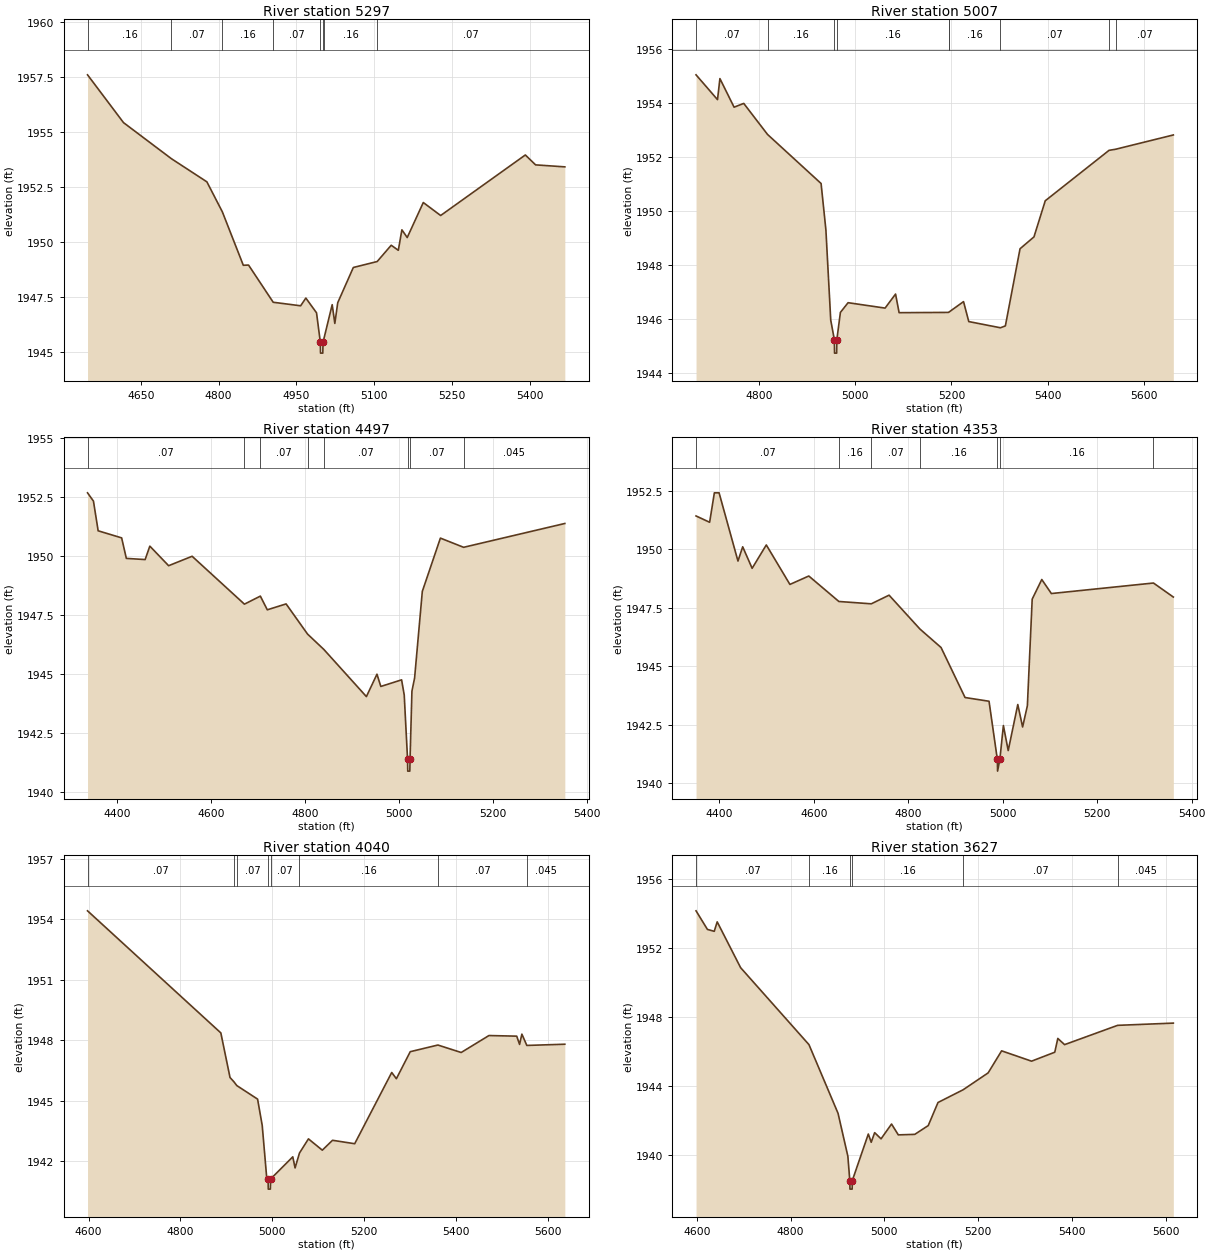
Type RM Length L Ch R = 1 ,5297    ,290,290,290
BEGIN DESCRIPTION:
Elm 01 20 5297.37
END DESCRIPTION:
XS GIS Cut Line= 3
      1526235.56      6813057.09      1526279.83      6812622.18
      1526160.03       6812153.4
#Sta/Elev= 30
  4547.1 1957.58  4616.5 1955.41    4709 1953.77  4777.4 1952.72  4807.2 1951.36
  4847.7 1948.93  4857.8 1948.94  4905.4 1947.25  4958.3 1947.09  4968.4 1947.44
    4989 1946.77  4996.3 1945.44  4996.7 1944.94  5001.1 1944.94  5001.5 1945.44
  5004.2 1945.69  5019.2 1947.14  5024.3 1946.29  5029.9 1947.23    5060 1948.83
    5106  1949.1  5133.1 1949.84  5146.8 1949.61  5153.7 1950.54    5164 1950.19
    5195 1951.78  5228.5 1951.19  5391.9 1953.94  5411.7 1953.49  5468.1  1953.4
#Mann= 8 ,-1 , 0
  4547.1     .16       0    4709     .07       0  4807.2     .16       0
  4905.4     .07       0  4996.3     .07       0  5001.5     .07       0
  5004.2     .16       0    5106     .07       0
Bank Sta=4996.3,5001.5
XS Rating Curve= 0 ,0
Exp/Cntr=0.3,0.1

Type RM Length L Ch R = 1 ,5007    ,510,510,510
BEGIN DESCRIPTION:
Elm 01 20 4908.84
END DESCRIPTION:
XS GIS Cut Line= 3
        1526515.      6813116.68       1526475.2       6812757.9
      1526225.16      6812176.91
#Sta/Elev= 30
  4668.4 1955.06  4713.1 1954.14  4718.1 1954.92  4747.6 1953.86  4767.7    1954
  4817.2 1952.85  4928.7 1951.03  4938.7 1949.31  4948.8 1945.96  4956.3 1945.24
  4956.7 1944.74  4961.1 1944.74  4961.5 1945.24  4968.9 1946.25  4984.9 1946.61
  5061.9 1946.41  5083.7 1946.93  5091.1 1946.24  5194.2 1946.25  5194.7 1946.26
  5225.2 1946.65  5236.1 1945.91  5302.1 1945.68  5312.3 1945.75  5342.8 1948.61
  5371.8 1949.05  5395.3 1950.39  5528.1 1952.26  5541.7  1952.3  5661.9 1952.83
#Mann= 9 ,-1 , 0
  4668.4     .07       0  4817.2     .16       0  4956.3     .07       0
  4961.5     .16       0  5194.2     .07       0  5194.7     .16       0
  5302.1     .07       0  5528.1    .045       0  5541.7     .07       0
Bank Sta=4956.3,4961.5
XS Rating Curve= 0 ,0
Exp/Cntr=0.3,0.1

Type RM Length L Ch R = 1 ,4497    ,144,144,144
BEGIN DESCRIPTION:
Elm 01 20 4512.27
END DESCRIPTION:
XS GIS Cut Line= 3
      1526619.23      6813080.55       1526619.8      6812582.78
      1526379.63      6812123.79
#Sta/Elev= 30
  4336.5 1952.67  4349.1 1952.32  4359.1 1951.06  4409.1 1950.76  4419.1 1949.89
  4459.1 1949.84  4469.1 1950.41  4509.1 1949.58  4559.1 1949.98  4670.4 1947.95
  4704.3 1948.29  4719.1 1947.71  4759.1 1947.96  4804.8 1946.68  4839.4 1946.03
    4930 1944.03  4952.5 1944.98  4960.7 1944.46  5004.9 1944.74  5010.5  1944.1
  5017.6 1941.37    5018 1940.87  5022.4 1940.87  5022.9 1941.37  5026.9 1944.26
  5032.6 1944.82    5049 1948.49  5087.5 1950.75  5136.9 1950.36  5352.3 1951.37
#Mann= 8 ,-1 , 0
  4336.5     .07       0  4670.4     .16       0  4704.3     .07       0
  4804.8     .16       0  4839.4     .07       0  5017.6     .07       0
  5022.9     .07       0  5136.9    .045       0
Bank Sta=5017.6,5022.9
XS Rating Curve= 0 ,0
Exp/Cntr=0.3,0.1

Type RM Length L Ch R = 1 ,4353    ,313,313,313
BEGIN DESCRIPTION:
Elm 01 20 4418.18
END DESCRIPTION:
XS GIS Cut Line= 3
      1526637.69      6813086.79      1526632.54      6812573.95
      1526719.55      6812083.67
#Sta/Elev= 30
  4350.4 1951.43  4379.2 1951.16  4389.2 1952.42  4399.2 1952.42  4439.2  1949.5
  4449.2 1950.11  4469.2 1949.19  4499.2 1950.19  4549.2  1948.5  4589.2 1948.86
  4652.9 1947.77  4721.5 1947.67  4759.2 1948.04  4824.6 1946.59  4869.3  1945.8
  4920.1 1943.66  4970.9  1943.5  4988.5 1941.01    4989 1940.51  4993.8 1941.01
  5001.3 1942.46  5011.5 1941.39  5031.8 1943.36    5042  1942.4  5052.1 1943.31
  5062.3 1947.87  5082.6 1948.71  5102.9 1948.11  5319.1 1948.56  5361.2 1947.96
#Mann= 7 ,-1 , 0
  4350.4     .07       0  4652.9     .16       0  4721.5     .07       0
  4824.6     .16       0  4988.5     .07       0  4993.8     .16       0
  5319.1    .045       0
Bank Sta=4988.5,4993.8
XS Rating Curve= 0 ,0
Exp/Cntr=0.3,0.1

Type RM Length L Ch R = 1 ,4040    ,413,413,413
BEGIN DESCRIPTION:
Elm 01 20 4040.19
END DESCRIPTION:
XS GIS Cut Line= 3
      1526831.92      6813077.96      1526816.29      6812682.08
      1526738.16      6812044.03
#Sta/Elev= 30
  4597.7 1954.41  4887.9 1948.36  4907.9 1946.15  4916.3 1945.94  4922.7 1945.75
  4967.9 1945.08    4978 1943.77    4988 1941.12  4990.7 1941.12  4991.2 1940.62
  4995.7 1940.62  4996.1 1941.12  5044.5 1942.22  5049.5 1941.67  5059.1 1942.41
  5078.6 1943.11  5108.8 1942.55    5131 1943.04  5179.3 1942.87  5259.9  1946.4
    5270 1946.09  5300.2 1947.43  5360.4 1947.76  5411.1 1947.39  5471.5 1948.23
    5532  1948.2  5538.2 1947.79  5543.2  1948.3    5554 1947.74  5636.7  1947.8
#Mann= 8 ,-1 , 0
  4597.7     .07       0  4916.3     .16       0  4922.7     .07       0
  4990.7     .07       0  4996.1     .07       0  5059.1     .16       0
  5360.4     .07       0    5554    .045       0
Bank Sta=4990.7,4996.1
XS Rating Curve= 0 ,0
Exp/Cntr=0.3,0.1

Type RM Length L Ch R = 1 ,3627    ,367,367,367
BEGIN DESCRIPTION:
Elm 01 20 3627.27
END DESCRIPTION:
XS GIS Cut Line= 3
      1527376.17      6812830.49       1527131.4       6812510.2
      1526740.77      6812036.24
#Sta/Elev= 30
  4598.6 1954.16  4622.9 1953.08  4637.4 1952.97  4643.7 1953.52  4693.6 1950.86
  4839.3 1946.39  4901.3  1942.4  4922.2 1939.91  4926.3  1938.5  4926.7    1938
  4931.3    1938  4931.7  1938.5  4965.8  1941.2    4972 1940.72  4979.3 1941.28
  4992.9 1940.92  5015.3 1941.78  5029.7 1941.15  5064.8 1941.18  5093.5 1941.69
  5114.3 1943.03  5167.9 1943.77  5221.2 1944.75  5249.9 1946.03  5313.7 1945.43
  5363.2 1945.95  5369.7 1946.75  5384.1 1946.39  5497.1 1947.51  5615.9 1947.64
#Mann= 6 ,-1 , 0
  4598.6     .07       0  4839.3     .16       0  4926.3     .07       0
  4931.7     .16       0  5167.9     .07       0  5497.1    .045       0
Bank Sta=4926.3,4931.7
XS Rating Curve= 0 ,0
Exp/Cntr=0.3,0.1

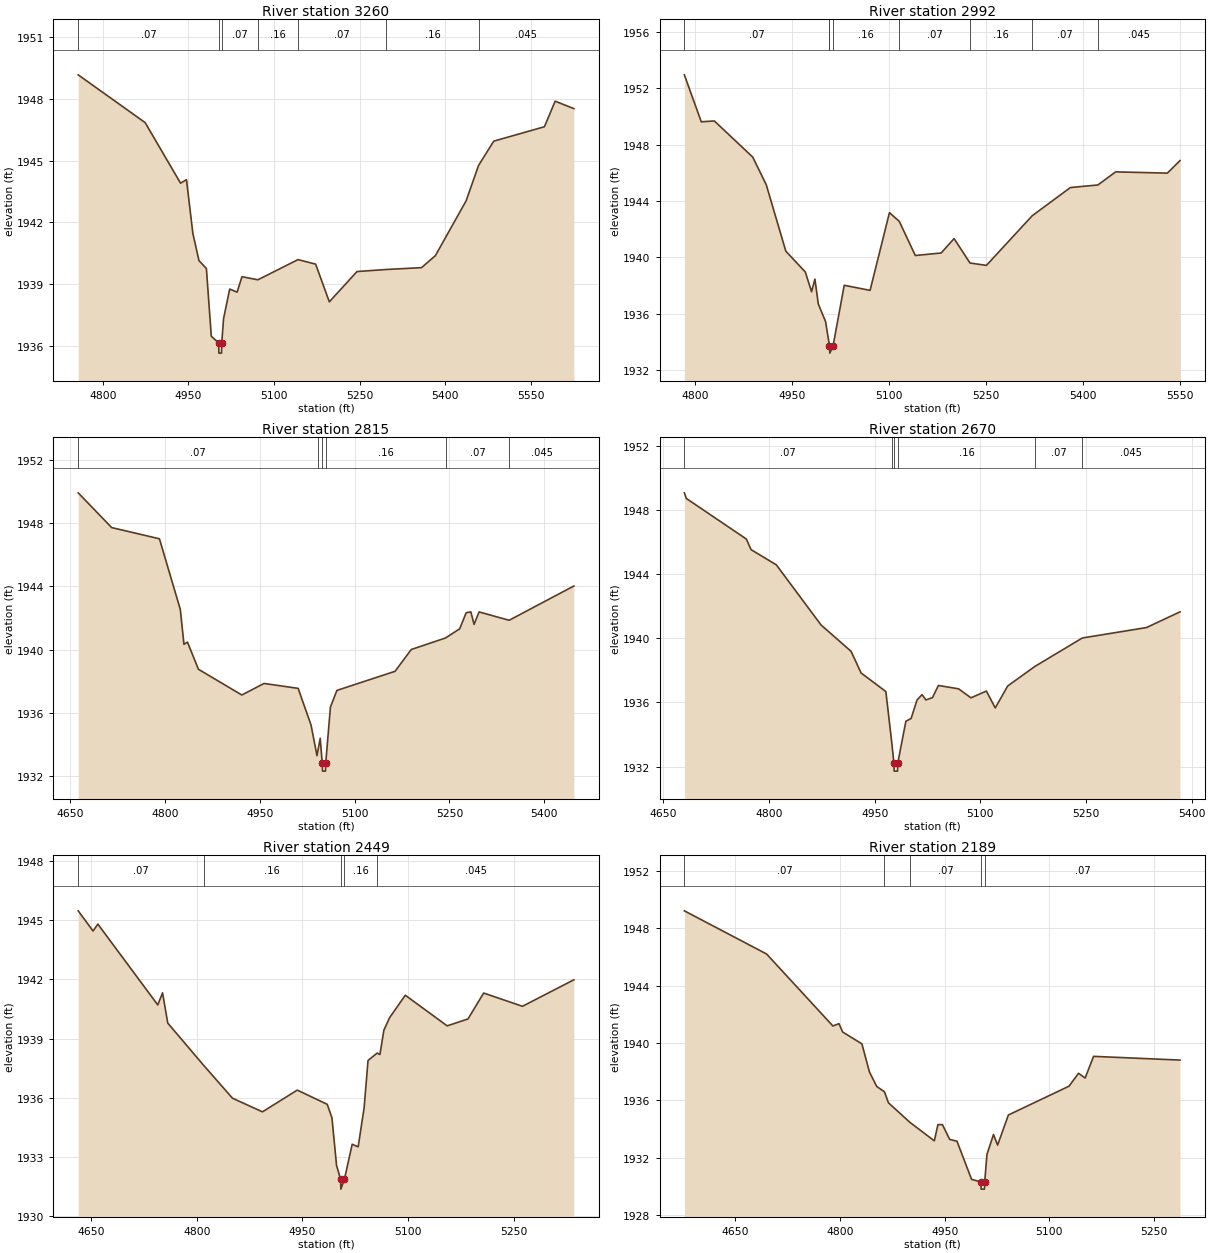
Type RM Length L Ch R = 1 ,3260    ,268,268,268
BEGIN DESCRIPTION:
Elm 01 20 3259.59
END DESCRIPTION:
XS GIS Cut Line= 3
      1527571.52      6812335.74      1527344.94      6812244.58
      1526764.49      6812012.92
#Sta/Elev= 30
  4756.6 1949.16    4874 1946.84  4936.1  1943.9  4946.5 1944.07  4957.7 1941.46
  4968.4 1940.14  4981.4 1939.76    4990 1936.47  5002.9 1936.15  5003.3 1935.65
  5007.9 1935.65  5008.4 1936.15  5011.5 1937.32  5022.3 1938.76  5035.3 1938.61
  5043.8 1939.36  5071.7 1939.21  5142.1 1940.19    5173 1939.97    5197 1938.14
  5245.5 1939.61  5296.8 1939.71  5358.6  1939.8  5382.9 1940.38  5436.8 1943.04
  5458.7 1944.76  5485.3 1945.94  5574.2 1946.64    5593 1947.88  5625.8 1947.52
#Mann= 7 ,-1 , 0
  4756.6     .07       0  5002.9     .07       0  5008.4     .07       0
  5071.7     .16       0  5142.1     .07       0  5296.8     .16       0
  5458.7    .045       0
Bank Sta=5002.9,5008.4
XS Rating Curve= 0 ,0
Exp/Cntr=0.3,0.1

Type RM Length L Ch R = 1 ,2992    ,177,177,177
BEGIN DESCRIPTION:
Elm 01 20 2992.29
END DESCRIPTION:
XS GIS Cut Line= 3
      1527561.08        6812005.      1527347.54      6811981.56
      1526795.42      6811973.75
#Sta/Elev= 30
  4783.6 1952.94  4809.8 1949.61    4830 1949.67  4889.4 1947.11  4910.4 1945.14
  4940.6 1940.44  4970.8 1938.96  4980.5 1937.56  4985.6 1938.46  4990.9 1936.69
  5002.2 1935.44  5007.6 1933.88  5008.2 1933.71  5008.7 1933.21  5013.7 1933.71
    5031 1938.02    5071 1937.66    5101 1943.17  5116.2 1942.55    5141 1940.13
    5181 1940.31    5201 1941.33  5225.6  1939.6    5251 1939.43  5321.9 1942.95
    5381 1944.95  5423.5 1945.13    5451 1946.06    5531 1945.97  5550.6 1946.86
#Mann= 8 ,-1 , 0
  4783.6     .07       0  5007.6     .16       0  5008.2     .07       0
  5013.7     .16       0  5116.2     .07       0  5225.6     .16       0
  5321.9     .07       0  5423.5    .045       0
Bank Sta=5008.2,5013.7
XS Rating Curve= 0 ,0
Exp/Cntr=0.3,0.1

Type RM Length L Ch R = 1 ,2815    ,145,145,145
BEGIN DESCRIPTION:
Elm 01 20 2815.31
END DESCRIPTION:
XS GIS Cut Line= 3
      1527571.46      6811973.73      1527269.42      6811833.12
      1526828.36      6811739.72
#Sta/Elev= 30
  4662.7 1949.92  4715.6 1947.72  4791.2 1947.01  4824.2 1942.54    4830 1940.33
  4835.5 1940.47  4852.9 1938.75  4921.5 1937.12  4956.6 1937.85  5010.6 1937.54
    5031 1935.22  5040.4 1933.28  5042.5 1933.73  5045.5 1934.38  5048.7  1932.8
  5049.2  1932.3  5053.8  1932.3  5054.2  1932.8  5061.7 1936.36  5071.9 1937.41
  5163.9 1938.62  5189.5    1940  5243.7 1940.73  5266.1 1941.31  5276.4 1942.33
  5283.8 1942.38  5288.9 1941.59  5296.8 1942.38  5344.3 1941.85  5446.7 1944.02
#Mann= 6 ,-1 , 0
  4662.7     .07       0  5042.5     .16       0  5048.7     .07       0
  5054.2     .16       0  5243.7     .07       0  5344.3    .045       0
Bank Sta=5048.7,5054.2
XS Rating Curve= 0 ,0
Exp/Cntr=0.3,0.1

Type RM Length L Ch R = 1 ,2670    ,221,221,221
BEGIN DESCRIPTION:
Elm 01 20 2669.72
END DESCRIPTION:
XS GIS Cut Line= 3
      1527592.32      6811934.67      1527355.35      6811721.14
      1527003.79      6811564.89
#Sta/Elev= 30
  4679.8 1949.07  4682.6 1948.72  4767.8 1946.19  4774.5 1945.53  4810.4 1944.58
  4873.9 1940.83  4916.5 1939.19  4930.7 1937.84  4965.9 1936.68  4974.5 1933.41
  4977.3 1932.22  4977.7 1931.72  4982.4 1931.72  4982.8 1932.22  4994.3 1934.83
  5001.7    1935  5010.1 1936.15  5017.2 1936.49  5022.7 1936.16    5032  1936.3
  5040.5 1937.06  5069.2 1936.85  5086.7 1936.29  5108.6 1936.71  5121.2 1935.66
  5138.9 1937.03  5177.6 1938.25  5244.8 1940.02  5335.9 1940.67  5383.5 1941.65
#Mann= 6 ,-1 , 0
  4679.8     .07       0  4974.5     .16       0  4977.3     .07       0
  4982.8     .16       0  5177.6     .07       0  5244.8    .045       0
Bank Sta=4977.3,4982.8
XS Rating Curve= 0 ,0
Exp/Cntr=0.3,0.1

Type RM Length L Ch R = 1 ,2449    ,260,260,260
BEGIN DESCRIPTION:
Elm 01 20 2449.227
END DESCRIPTION:
XS GIS Cut Line= 3
      1527628.38      6811834.01      1527381.32      6811560.87
      1527080.04      6811413.02
#Sta/Elev= 30
  4631.7 1945.46  4652.8 1944.44  4659.6 1944.79  4744.7  1940.7  4751.5 1941.31
  4758.9 1939.78  4809.7 1937.65  4850.8 1935.98  4893.4 1935.29  4942.8 1936.39
  4985.4 1935.67  4992.1 1934.98  4998.6 1932.58  5004.3 1931.88  5004.7 1931.38
  5009.8 1931.88  5020.8 1933.65  5029.3 1933.52  5037.7 1935.48  5043.3 1937.89
  5056.2 1938.26  5060.2 1938.19  5065.8 1939.42  5073.9 1940.05  5096.2 1941.19
  5155.7 1939.64  5185.3 1939.99  5207.5  1941.3  5262.6 1940.63  5335.6 1941.97
#Mann= 5 ,-1 , 0
  4631.7     .07       0  4809.7     .16       0  5004.3     .07       0
  5009.8     .16       0  5056.2    .045       0
Bank Sta=5004.3,5009.8
XS Rating Curve= 0 ,0
Exp/Cntr=0.3,0.1

Type RM Length L Ch R = 1 ,2189    ,279,279,279
BEGIN DESCRIPTION:
Elm 01 20 2189.201
END DESCRIPTION:
XS GIS Cut Line= 3
      1527725.57      6811941.61       1527602.3      6811536.97
      1527451.49      6811292.67
#Sta/Elev= 30
    4577 1949.22  4694.8 1946.21  4789.8 1941.19  4798.5 1941.35  4803.8 1940.77
  4831.4 1939.94  4842.1 1937.99  4852.6 1936.97  4863.7  1936.6  4869.4 1935.83
  4900.1 1934.47  4935.1 1933.18  4940.3 1934.31  4946.7 1934.31  4957.1 1933.28
  4967.6 1933.15  4988.5 1930.49  5001.8 1930.31  5002.2 1929.81  5006.9 1929.81
  5007.3 1930.31  5010.5 1932.23  5019.9 1933.62  5025.8 1932.88  5041.2 1934.98
  5128.1 1936.99  5141.7 1937.89  5151.2 1937.56  5163.3 1939.07  5287.1 1938.81
#Mann= 5 ,-1 , 0
    4577     .07       0  4863.7     .16       0  4900.1     .07       0
  5001.8     .07       0  5007.3     .07       0
Bank Sta=5001.8,5007.3
XS Rating Curve= 0 ,0
Exp/Cntr=0.3,0.1

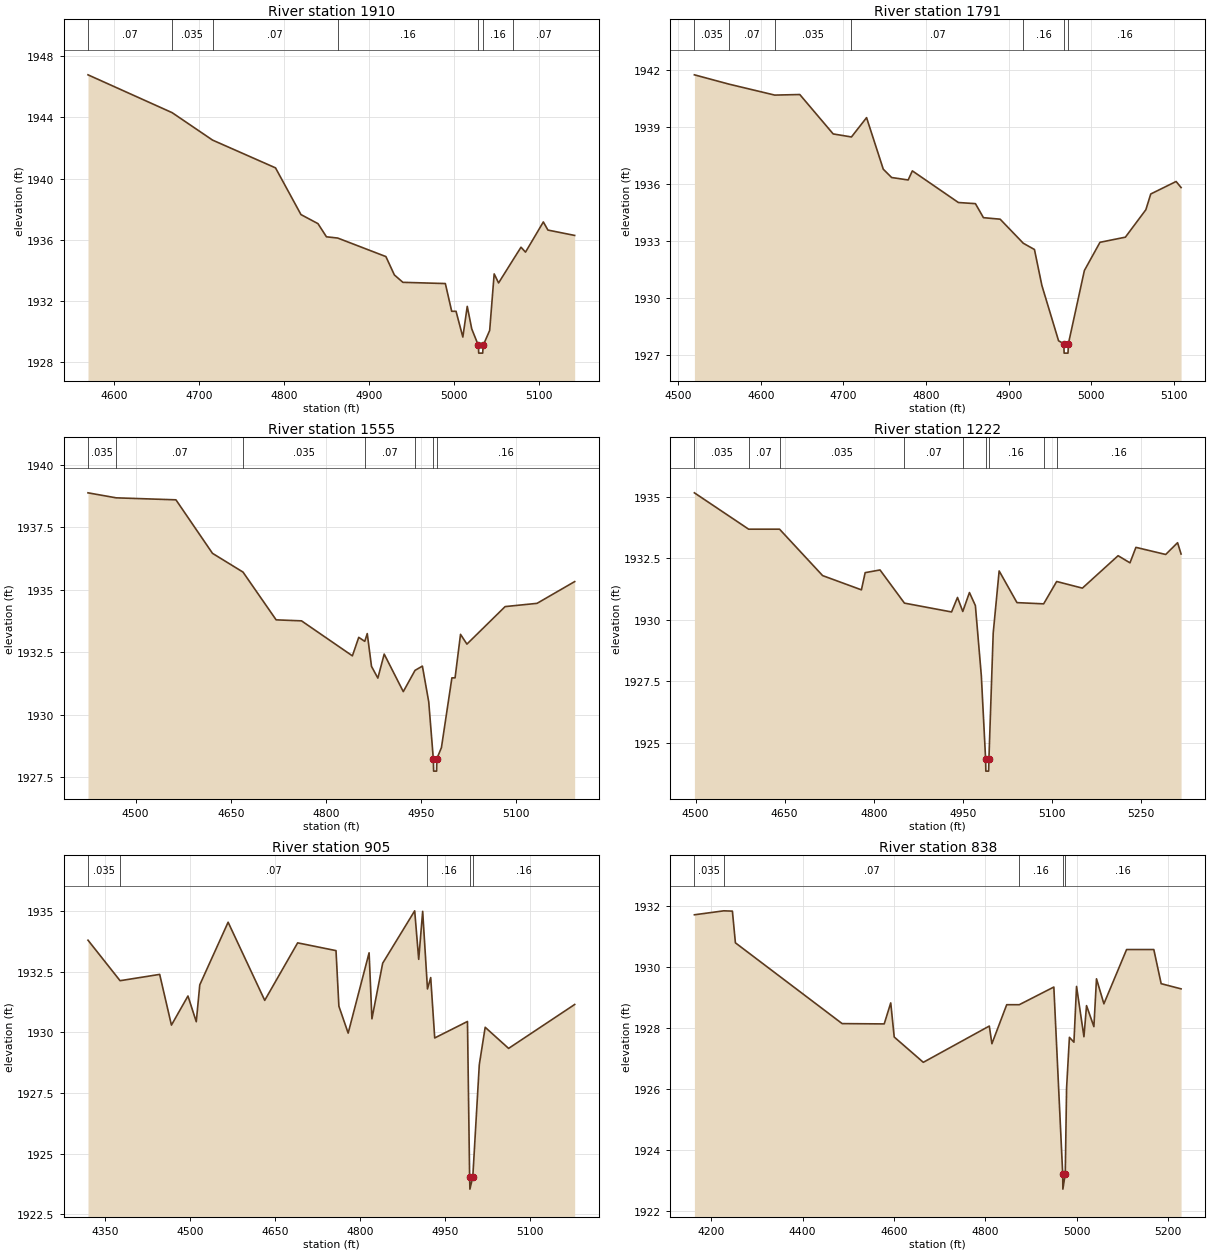
Type RM Length L Ch R = 1 ,1910    ,119,119,119
BEGIN DESCRIPTION:
Elm 01 20 1909.739
END DESCRIPTION:
XS GIS Cut Line= 3
      1527815.86      6811868.74      1527825.01      6811438.14
      1527780.08      6811303.01
#Sta/Elev= 30
  4569.3 1946.77  4668.4  1944.3    4716 1942.51  4790.1  1940.7  4820.1 1937.65
  4840.1 1937.06  4850.1  1936.2  4863.3 1936.12  4920.1 1934.91  4930.1 1933.71
  4940.1 1933.23  4990.1 1933.15  4997.6 1931.34  5002.7 1931.34  5010.7 1929.66
  5015.9 1931.66  5021.2 1930.19    5029 1929.11  5029.4 1928.61  5034.1 1928.61
  5034.6 1929.11  5042.3 1930.09  5047.6 1933.78  5052.8 1933.19  5070.3 1934.74
  5079.2 1935.52  5084.5  1935.2  5105.5 1937.17  5110.9 1936.64  5142.4 1936.29
#Mann= 7 ,-1 , 0
  4569.3     .07       0  4668.4    .035       0    4716     .07       0
  4863.3     .16       0    5029     .07       0  5034.6     .16       0
  5070.3     .07       0
Bank Sta=5029,5034.6
XS Rating Curve= 0 ,0
Exp/Cntr=0.3,0.1

Type RM Length L Ch R = 1 ,1791    ,236,236,236
BEGIN DESCRIPTION:
Elm 01 20 1817.756
END DESCRIPTION:
XS GIS Cut Line= 3
      1528006.62      6811884.29      1527943.57        6811435.
      1527897.74       6811307.9
#Sta/Elev= 30
  4519.7 1941.77  4561.4 1941.28  4616.9  1940.7  4647.2 1940.73  4687.6 1938.65
  4709.7 1938.49    4728 1939.51  4748.2 1936.79  4758.3 1936.35  4778.3 1936.22
  4783.4  1936.7  4839.1 1935.03  4859.7 1934.97  4869.4 1934.23  4889.6 1934.15
  4917.6 1932.88  4931.1 1932.55  4940.1 1930.65  4960.3 1927.73  4966.6 1927.58
    4967 1927.08  4971.7 1927.08  4972.2 1927.58  4991.5 1931.44  5010.4 1932.93
  5041.1  1933.2  5065.9 1934.65  5071.8 1935.48  5102.5 1936.14  5108.5 1935.82
#Mann= 7 ,-1 , 0
  4519.7    .035       0  4561.4     .07       0  4616.9    .035       0
  4709.7     .07       0  4917.6     .16       0  4966.6     .07       0
  4972.2     .16       0
Bank Sta=4966.6,4972.2
XS Rating Curve= 0 ,0
Exp/Cntr=0.3,0.1

Type RM Length L Ch R = 1 ,1555    ,333,333,333
BEGIN DESCRIPTION:
Elm 01 20 1554.905
END DESCRIPTION:
XS GIS Cut Line= 3
        1528111.      6811913.81      1528149.02      6811340.17
      1528130.77      6811148.94
#Sta/Elev= 30
  4425.1 1938.87  4469.4 1938.67  4563.7 1938.59  4621.3 1936.45  4669.4  1935.7
  4721.6 1933.79  4761.6 1933.75  4841.8 1932.35  4851.8 1933.09  4861.3 1932.93
  4865.2 1933.24  4871.9 1931.93  4881.9 1931.46  4891.9 1932.42    4922 1930.92
  4940.5 1931.77  4952.1 1931.94  4962.1 1930.51  4969.3 1928.24  4969.8 1927.74
  4974.5 1927.74  4974.9 1928.24  4982.1 1928.68  4998.6 1931.47  5003.6 1931.47
  5012.2 1933.21  5022.3 1932.82  5082.5 1934.32  5132.8 1934.45  5192.1 1935.32
#Mann= 7 ,-1 , 0
  4425.1    .035       0  4469.4     .07       0  4669.4    .035       0
  4861.3     .07       0  4940.5     .16       0  4969.3     .07       0
  4974.9     .16       0
Bank Sta=4969.3,4974.9
XS Rating Curve= 0 ,0
Exp/Cntr=0.3,0.1

Type RM Length L Ch R = 1 ,1222    ,317,317,317
BEGIN DESCRIPTION:
Elm 01 20 1187.933
END DESCRIPTION:
XS GIS Cut Line= 3
      1528367.65      6811827.38      1528459.18      6811520.14
      1528437.26      6811022.11
#Sta/Elev= 30
  4498.1 1935.17  4589.4 1933.69  4641.4 1933.69  4713.9  1931.8  4779.2 1931.22
  4785.5 1931.92  4810.5 1932.03  4851.6 1930.68  4930.9 1930.32  4940.9 1930.91
  4949.8 1930.34    4961 1931.11    4971 1930.58    4981 1927.73  4988.2 1924.34
  4988.6 1923.84  4993.3 1923.84  4993.8 1924.34    5001 1929.46    5011 1931.99
    5041  1930.7  5085.9 1930.65  5107.8 1931.56  5151.1 1931.29  5211.2 1932.61
  5231.2 1932.32  5241.2 1932.95  5291.3 1932.66  5311.3 1933.14  5317.2 1932.68
#Mann= 9 ,-1 , 0
  4498.1    .035       0  4589.4     .07       0  4641.4    .035       0
  4851.6     .07       0  4949.8     .16       0  4988.2     .07       0
  4993.8     .16       0  5085.9     .07       0  5107.8     .16       0
Bank Sta=4988.2,4993.8
XS Rating Curve= 0 ,0
Exp/Cntr=0.3,0.1

Type RM Length L Ch R = 1 ,905     ,67,67,67
BEGIN DESCRIPTION:
Elm 01 20 1.0
END DESCRIPTION:
XS GIS Cut Line= 5
      1528467.25      6811777.69      1528804.09      6811527.99
      1528779.47      6811392.34      1528737.88      6811349.96
      1528667.87      6811116.47
#Sta/Elev= 30
  4319.1  1933.8  4375.8 1932.13  4445.8 1932.39  4466.6  1930.3  4495.8  1931.5
  4510.5 1930.44  4516.7 1931.96  4566.8 1934.54  4631.5 1931.32  4689.7 1933.69
  4757.5 1933.37  4762.6 1931.08    4779 1929.97    4816 1933.28    4821 1930.56
    4840 1932.85  4896.6 1935.01  4903.7 1933.01  4910.7 1934.99  4919.2 1931.79
  4924.9 1932.26    4932 1929.77  4989.9 1930.45  4993.7 1924.04  4994.2 1923.54
  4999.3 1924.04  5010.8 1928.67  5021.2 1930.21  5062.6 1929.34  5179.4 1931.15
#Mann= 5 ,-1 , 0
  4319.1    .035       0  4375.8     .07       0  4919.2     .16       0
  4993.7     .07       0  4999.3     .16       0
Bank Sta=4993.7,4999.3
XS Rating Curve= 0 ,0
Exp/Cntr=0.3,0.1

Type RM Length L Ch R = 1 ,838     ,0,0,0
BEGIN DESCRIPTION:
Elm 01 20 838.045
END DESCRIPTION:
XS GIS Cut Line= 3
      1528541.56       6811931.2      1528909.61      6811504.13
      1528670.04      6811063.18
#Sta/Elev= 30
  4163.1 1931.71  4227.5 1931.84  4246.3 1931.83  4252.9 1930.79  4486.6 1928.14
  4578.7 1928.13    4593 1928.82  4600.6  1927.7  4664.3 1926.87  4808.8 1928.06
  4814.5 1927.48  4846.9 1928.76  4874.4 1928.76  4950.1 1929.34  4969.5 1923.21
  4969.9 1922.71  4975.1 1923.21    4978 1926.02  4984.2 1927.69  4994.1 1927.53
  4999.8 1929.36    5016 1927.71  5021.7 1928.73  5037.8 1928.04  5043.5 1929.61
  5059.7 1928.79  5109.4 1930.57    5169 1930.57  5185.1 1929.45  5228.7 1929.28
#Mann= 5 ,-1 , 0
  4163.1    .035       0  4227.5     .07       0  4874.4     .16       0
  4969.5     .07       0  4975.1     .16       0
Bank Sta=4969.5,4975.1
XS Rating Curve= 0 ,0
Exp/Cntr=0.3,0.1

Chan Stop Cuts=-1
Use User Specified Reach Order=0
Composite Channel Slope=5