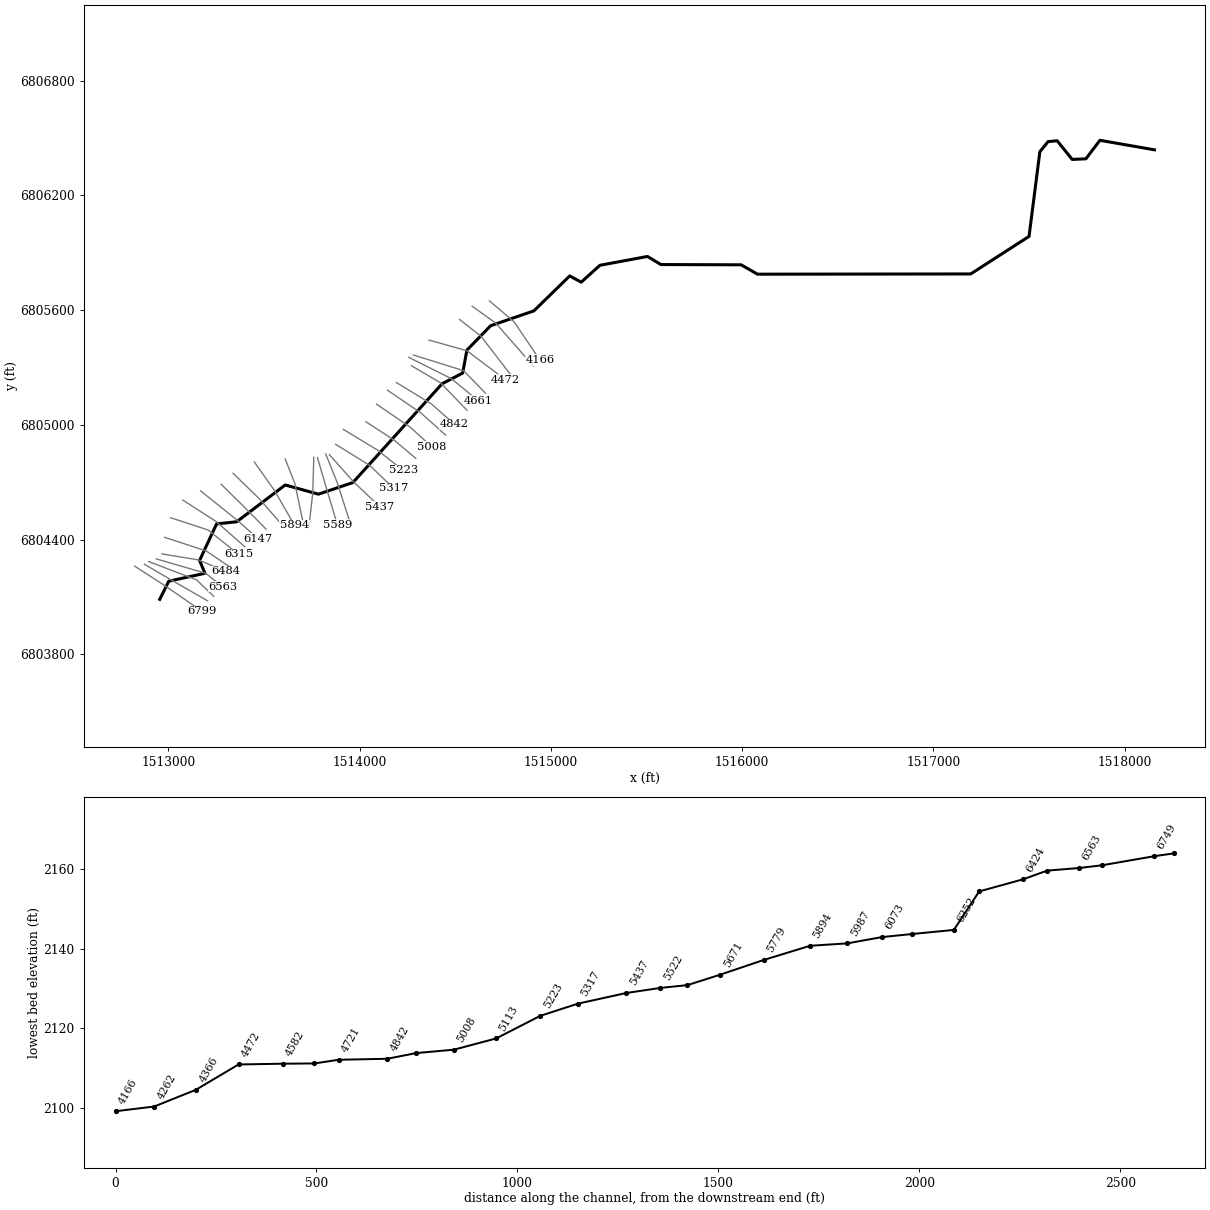
--- Elm 01 21.prj (project) ---

Proj Title=Elm 01 21 Base Level Engineering
Current Plan=p01
Default Exp/Contr=0.3,0.1
English Units
Geom File=g01
Flow File=f01
Plan File=p01
Y Axis Title=Elevation
X Axis Title(PF)=Main Channel Distance
X Axis Title(XS)=Station
BEGIN DESCRIPTION:
Elm 01 21
END DESCRIPTION:
DSS Export Rating Curves= 0
DSS Export Rating Curve Sorted= 0
DSS Export Volume Flow Curves= 0
DXF OffsetX= 0
DXF OffsetY= 0
DXF ScaleX= 1
DXF ScaleY= 10

--- Elm 01 21.p01 (plan) ---

Plan Title=Multiple Run
Program Version=4.10
Short Identifier=Multiple
Geom File=g01
Flow File=f01
Subcritical Flow
K Sum by GR= 0
Std Step Tol= 0.01
Critical Tol= 0.01
Num of Std Step Trials= 20
Max Error Tol= 0.3
Flow Tol Ratio= 0.001
Split Flow NTrial= 30
Split Flow Tol= 0.02
Split Flow Ratio= 0.02
Log Output Level= 0
Friction Slope Method= 1
Unsteady Friction Slope Method= 2
Unsteady Bridges Friction Slope Method= 1
Parabolic Critical Depth
Global Vel Dist= 1 , 1 , 1
Global Log Level= 0
CheckData=True
Encroach Param=-1 ,0,0, 0
BEGIN DESCRIPTION:
Multiple Run
END DESCRIPTION:
Computation Interval=1HOUR
Output Interval=1HOUR
Run HTab= 0
Run UNet= 0
Run PostProcess= 0
Run WQNet= 0
UNET Theta= 1
UNET Theta Warmup= 1
UNET ZTol= 0.02
UNET ZSATol= 0.05
UNET MxIter= 20
UNET MaxInSteps= 0
UNET DtIC= 0
UNET DtMin= 0
UNET MaxCRTS= 20
UNET WFStab= 2
UNET SFStab= 1
UNET WFX= 1
UNET SFX= 1
UNET DSS MLevel= 4
UNET DZMax Abort= 100
UNET Convert EG Bridges= 0
UNET Use Existing IB Tables=-1
UNET Froude Reduction=False
UNET Froude Limit= 1
UNET Froude Power= 10
UNET Time Slicing=0,0, 5
UNET Junction Losses=0
Instantaneous Interval=1HOUR
Write IC File= 0
Write IC File at Sim End=0
Echo Input=False
Echo Parameters=False
Echo Output=False
Write Detailed= 0
WQ AD Non Conservative
WQ ULTIMATE=-1
WQ Max Comp Step=1HOUR
WQ Output Interval=15MIN
WQ Output Selected Increments= 0
WQ Output face flow=0
WQ Output face velocity=0
WQ Output face area=0
WQ Output face dispersion=0
WQ Output cell volume=0
WQ Output cell surface area=0
WQ Output cell continuity=0
WQ Output cumulative cell continuity=0
WQ Output face conc=0
WQ Output face dconc_dx=0
WQ Output face courant=0
WQ Output face peclet=0
WQ Output face adv mass=0
WQ Output face disp mass=0
WQ Output cell mass=0
WQ Output cell source sink temp=0
WQ Output cell source sink nsm=0
WQ Output MaxMinRange=-1
WQ Daily Max Min Mean=-1
WQ Daily Range=0
WQ Daily Time=0
WQ Create Restart=0
WQ Fixed Restart=0
WQ System Summary=0
WQ Use Fixed Temperature=0
Sorting and Armoring Iterations= 10
XS Update Threshold= 0.02
Hydraulics Update Threshold= 0.02
Energy Slope Method= 1
Volume Change Method= 0
XS Weighting Method= 0
Number of US Weighted Cross Sections= 1
Number of DS Weighted Cross Sections= 1
Upstream XS Weight=0.25
Main XS Weight=0.5
Downstream XS Weight=0.25
Number of DS XS's Weighted with US Boundary= 1
Upstream Boundary Weight= 1
Weight of XSs Associated with US Boundary= 0
Number of US XS's Weighted with DS Boundary= 1
Downstream Boundary Weight= 0.5
Weight of XSs Associated with DS Boundary= 0.5
Sediment Output Level= 4
Mass or Volume Output= 0
Output Increment Type= 1
Profile and TS Output Increment= 10
XS Output Flag= 0
XS Output Increment= 10
Disregard all LS=0
Disregard all Conn=0
Disregard all Breaches=0
Disregard all Pumps=0

--- Elm 01 21.f01 (steady flow) ---

Flow Title=Multiple
Number of Profiles=7
Profile Names=10-year,25-year,50-year,1pct_min,100-year,1pct_plu,500-year
River Rch & RM= Elm 01 21,Reach-1,6799
     360     522     662     522     837    1150    1350
Boundary for River Rch & Prof#=Elm 01 21,Reach-1,1
Up Type=0
Dn Type=3
Dn Slope=0.005
Boundary for River Rch & Prof#=Elm 01 21,Reach-1,2
Up Type=0
Dn Type=3
Dn Slope=0.005
Boundary for River Rch & Prof#=Elm 01 21,Reach-1,3
Up Type=0
Dn Type=3
Dn Slope=0.005
Boundary for River Rch & Prof#=Elm 01 21,Reach-1,4
Up Type=0
Dn Type=3
Dn Slope=0.005
Boundary for River Rch & Prof#=Elm 01 21,Reach-1,5
Up Type=0
Dn Type=3
Dn Slope=0.005
Boundary for River Rch & Prof#=Elm 01 21,Reach-1,6
Up Type=0
Dn Type=3
Dn Slope=0.005
Boundary for River Rch & Prof#=Elm 01 21,Reach-1,7
Up Type=0
Dn Type=3
Dn Slope=0.005

--- Elm 01 21.g01 (geometry) ---

Geom Title=Existing Conditions
Program Version=4.10

River Reach=Elm 01 21       ,Reach-1
Reach XY= 30
        1512955.        6804088.      1513002.31      6804182.73
      1513191.53      6804224.24      1513163.29      6804291.21
      1513252.29      6804482.59      1513357.42      6804493.53
      1513610.97      6804685.86      1513784.82      6804637.72
      1513964.81      6804698.51      1514431.17      6805215.14
      1514538.69      6805270.87      1514560.53      6805390.42
      1514684.84      6805518.37      1514911.06      6805596.14
      1515098.33       6805778.7      1515158.33      6805746.02
      1515256.46      6805834.44        1515505.      6805880.44
      1515574.98      6805838.18       1515994.5      6805836.78
      1516079.92       6805787.8      1517194.56      6805789.06
      1517499.55      6805985.53        1517556.      6806427.76
      1517598.92       6806480.8      1517646.45       6806485.4
      1517725.11      6806387.69      1517796.65        6806391.
      1517870.05      6806487.67        1518155.        6806438.

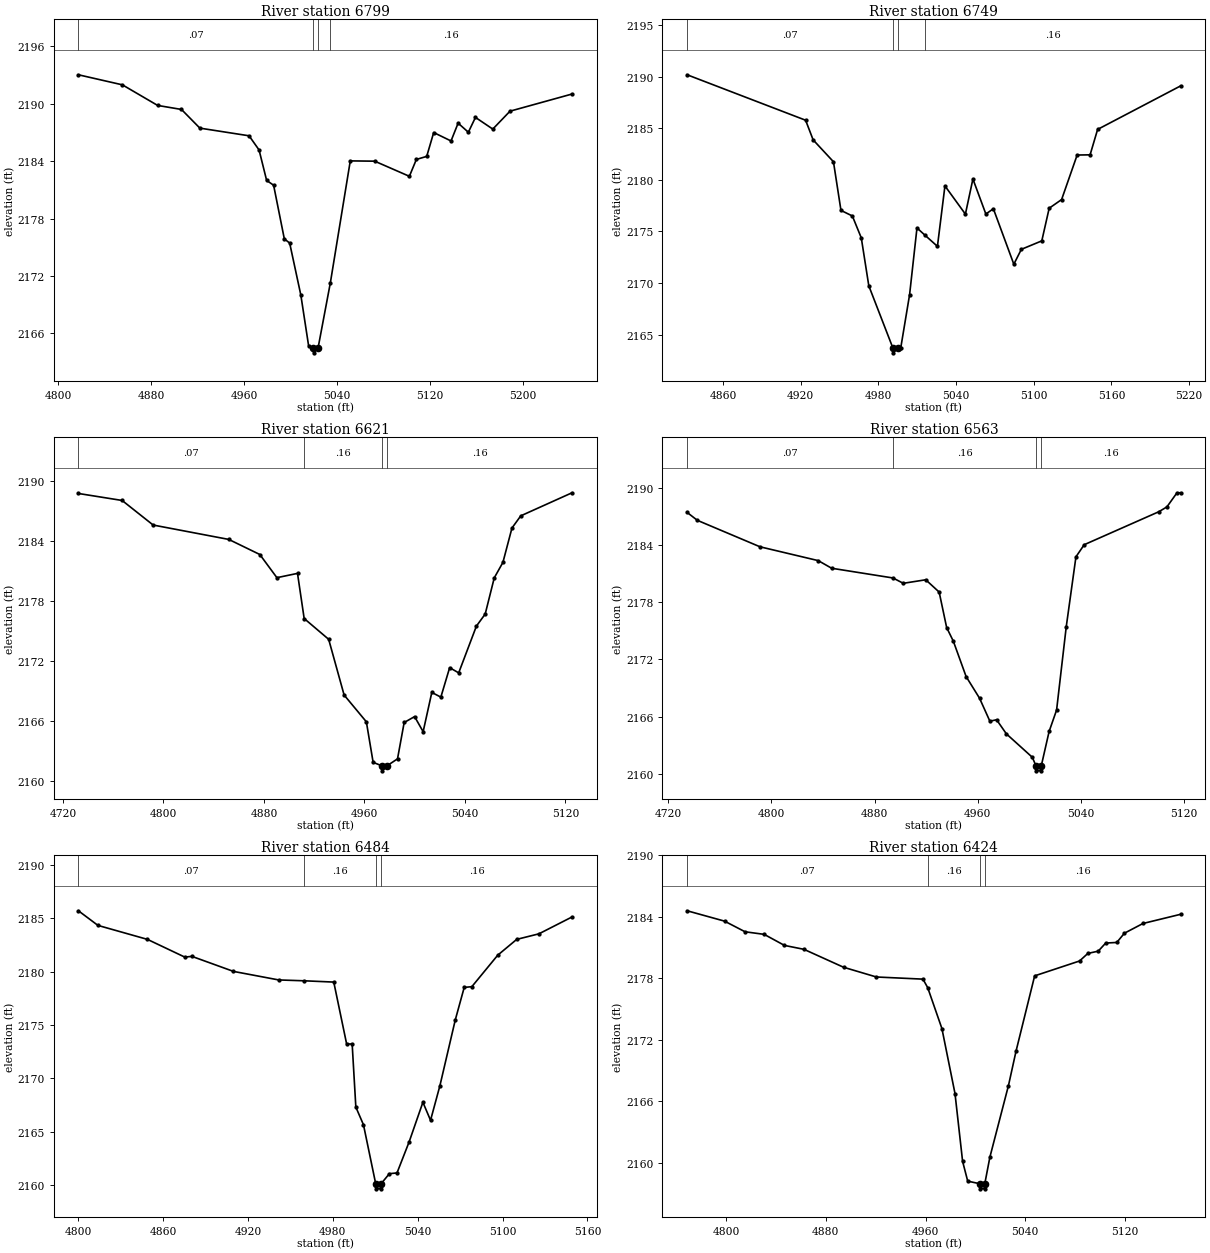
Type RM Length L Ch R = 1 ,6799    ,50,50,50
BEGIN DESCRIPTION:
Elm 01 21 6798.965
END DESCRIPTION:
XS GIS Cut Line= 3
      1512824.52      6804261.08      1512977.76      6804162.15
      1513176.99      6804024.95
#Sta/Elev= 30
  4817.6 2193.01  4855.4 2191.96  4885.7 2189.81  4906.2 2189.39    4922 2187.44
  4964.3 2186.64  4972.9 2185.16  4979.4 2181.98  4985.4 2181.48  4994.6 2175.88
  4999.2 2175.44  5008.8 2170.01  5015.5  2164.7  5019.6 2164.48  5019.8 2163.98
  5023.6 2164.48  5034.2 2171.31  5051.3 2184.02  5072.3 2183.99  5102.1 2182.41
  5108.1 2184.17    5117 2184.49    5123 2186.98  5137.9  2186.1    5144 2187.96
  5152.8 2187.01  5158.9 2188.56  5173.8 2187.34  5188.6 2189.21  5241.9    2191
#Mann= 4 ,-1 , 0
  4817.6     .07       0  5019.6     .07       0  5023.6     .07       0
  5034.2     .16       0
Bank Sta=5019.6,5023.6
XS Rating Curve= 0 ,0
Exp/Cntr=0.3,0.1

Type RM Length L Ch R = 1 ,6749    ,128,128,128
BEGIN DESCRIPTION:
Elm 01 21 6749.17
END DESCRIPTION:
XS GIS Cut Line= 3
      1512874.85      6804271.51      1513017.25      6804188.16
      1513204.75      6804080.52
#Sta/Elev= 30
  4832.3 2190.17  4923.8 2185.77  4929.6 2183.87  4945.3 2181.75  4951.1 2177.04
  4959.9  2176.5  4966.8 2174.38  4972.6 2169.74  4991.1 2163.75  4991.3 2163.25
  4995.1 2163.75  4997.3 2163.75  5004.1 2168.88  5009.8 2175.34  5015.8 2174.66
  5025.6 2173.56  5031.4 2179.41  5047.2 2176.68    5053 2180.08    5063 2176.69
  5068.8  2177.2  5084.6 2171.83  5090.4 2173.27  5106.2 2174.09  5111.9 2177.25
  5121.5 2178.09  5133.5  2182.4  5143.5 2182.42  5149.3 2184.88  5213.5  2189.1
#Mann= 4 ,-1 , 0
  4832.3     .07       0  4991.1     .07       0  4995.1     .07       0
  5015.8     .16       0
Bank Sta=4991.1,4995.1
XS Rating Curve= 0 ,0
Exp/Cntr=0.3,0.1

Type RM Length L Ch R = 1 ,6621    ,58,58,58
BEGIN DESCRIPTION:
Elm 01 21 6621.01
END DESCRIPTION:
XS GIS Cut Line= 3
      1512897.42      6804285.39      1513147.45      6804189.89
      1513237.74      6804103.08
#Sta/Elev= 30
  4732.3 2188.77  4767.1 2188.07  4791.8 2185.61    4852 2184.17  4876.7 2182.66
  4890.3 2180.34  4906.7 2180.77    4912 2176.25  4931.5 2174.17  4943.8 2168.59
  4961.5 2165.91  4966.9 2161.85  4973.9  2161.5  4974.2    2161  4977.9  2161.5
  4986.3  2162.2  4991.6 2165.84  4999.9 2166.43  5006.7 2164.92  5013.6 2168.85
  5020.8 2168.38  5027.8 2171.33    5035 2170.81  5049.1 2175.49  5056.1  2176.7
  5063.3 2180.32  5070.2 2181.87  5077.4 2185.31  5084.4 2186.53  5125.2 2188.84
#Mann= 4 ,-1 , 0
  4732.3     .07       0    4912     .16       0  4973.9     .07       0
  4977.9     .16       0
Bank Sta=4973.9,4977.9
XS Rating Curve= 0 ,0
Exp/Cntr=0.3,0.1

Type RM Length L Ch R = 1 ,6563    ,79,79,79
BEGIN DESCRIPTION:
Elm 01 21 6563.16
END DESCRIPTION:
XS GIS Cut Line= 3
      1512937.43      6804299.26      1513194.33      6804224.61
      1513284.61      6804153.43
#Sta/Elev= 30
  4734.8 2187.42  4742.7 2186.59  4791.3 2183.81  4836.4 2182.36  4846.8 2181.56
  4894.3 2180.54  4902.3 2179.98  4919.7 2180.35  4930.1 2179.06  4935.9 2175.34
  4941.1  2173.9    4951 2170.19  4961.4 2167.92  4969.4 2165.51  4974.6 2165.66
  4982.2 2164.18  5002.3 2161.72  5005.2  2160.8  5005.5  2160.3    5009  2160.3
  5009.2  2160.8  5015.3 2164.43  5021.1 2166.68  5028.6 2175.44  5036.1 2182.76
  5042.5 2184.03  5100.3 2187.49  5106.6    2188  5114.4 2189.48  5117.3 2189.48
#Mann= 4 ,-1 , 0
  4734.8     .07       0  4894.3     .16       0  5005.2     .07       0
  5009.2     .16       0
Bank Sta=5005.2,5009.2
XS Rating Curve= 0 ,0
Exp/Cntr=0.3,0.1

Type RM Length L Ch R = 1 ,6484    ,60,60,60
BEGIN DESCRIPTION:
Elm 01 21 6484.17
END DESCRIPTION:
XS GIS Cut Line= 3
      1512966.87      6804325.31      1513157.87      6804294.06
      1513301.02       6804233.7
#Sta/Elev= 30
  4800.2  2185.7    4814 2184.33    4849 2183.02  4875.4 2181.36  4880.4 2181.43
  4909.8 2180.02  4941.8 2179.22  4959.9 2179.14  4980.7 2179.02  4989.8 2173.22
  4993.7 2173.22  4996.3 2167.31  5001.7 2165.65  5010.3 2160.15  5010.6 2159.65
  5014.1 2159.65  5014.3 2160.15    5020 2161.07  5025.4 2161.14    5034 2164.06
  5043.7 2167.76  5049.1 2166.07  5055.7  2169.3  5066.6 2175.48  5072.9 2178.52
  5078.3 2178.59  5096.6 2181.54    5110 2183.02  5125.7 2183.54  5149.1 2185.12
#Mann= 4 ,-1 , 0
  4800.2     .07       0  4959.9     .16       0  5010.3     .07       0
  5014.3     .16       0
Bank Sta=5010.3,5014.3
XS Rating Curve= 0 ,0
Exp/Cntr=0.3,0.1

Type RM Length L Ch R = 1 ,6424    ,109,109,109
BEGIN DESCRIPTION:
Elm 01 21 6423.89
END DESCRIPTION:
XS GIS Cut Line= 3
      1512980.77      6804412.12       1513197.8      6804340.93
      1513336.71      6804247.17
#Sta/Elev= 30
  4768.7 2184.59  4798.7 2183.58  4815.2 2182.54  4830.5 2182.29  4846.8 2181.21
  4862.4 2180.83  4894.2 2179.08  4920.5 2178.13  4957.9 2177.92  4961.7 2177.09
  4973.1  2173.1  4983.6 2166.76  4989.7 2160.14  4993.8 2158.21  5003.5 2157.96
  5003.8 2157.46  5007.3 2157.46  5007.5 2157.96  5011.6 2160.56  5026.5 2167.54
  5032.6 2170.91  5047.5 2178.24  5083.5 2179.69  5090.2 2180.43  5098.5 2180.65
  5104.5 2181.44  5113.4  2181.5  5119.5  2182.4  5134.4 2183.35  5164.7 2184.25
#Mann= 4 ,-1 , 0
  4768.7     .07       0  4961.7     .16       0  5003.5     .07       0
  5007.5     .16       0
Bank Sta=5003.5,5007.5
XS Rating Curve= 0 ,0
Exp/Cntr=0.3,0.1

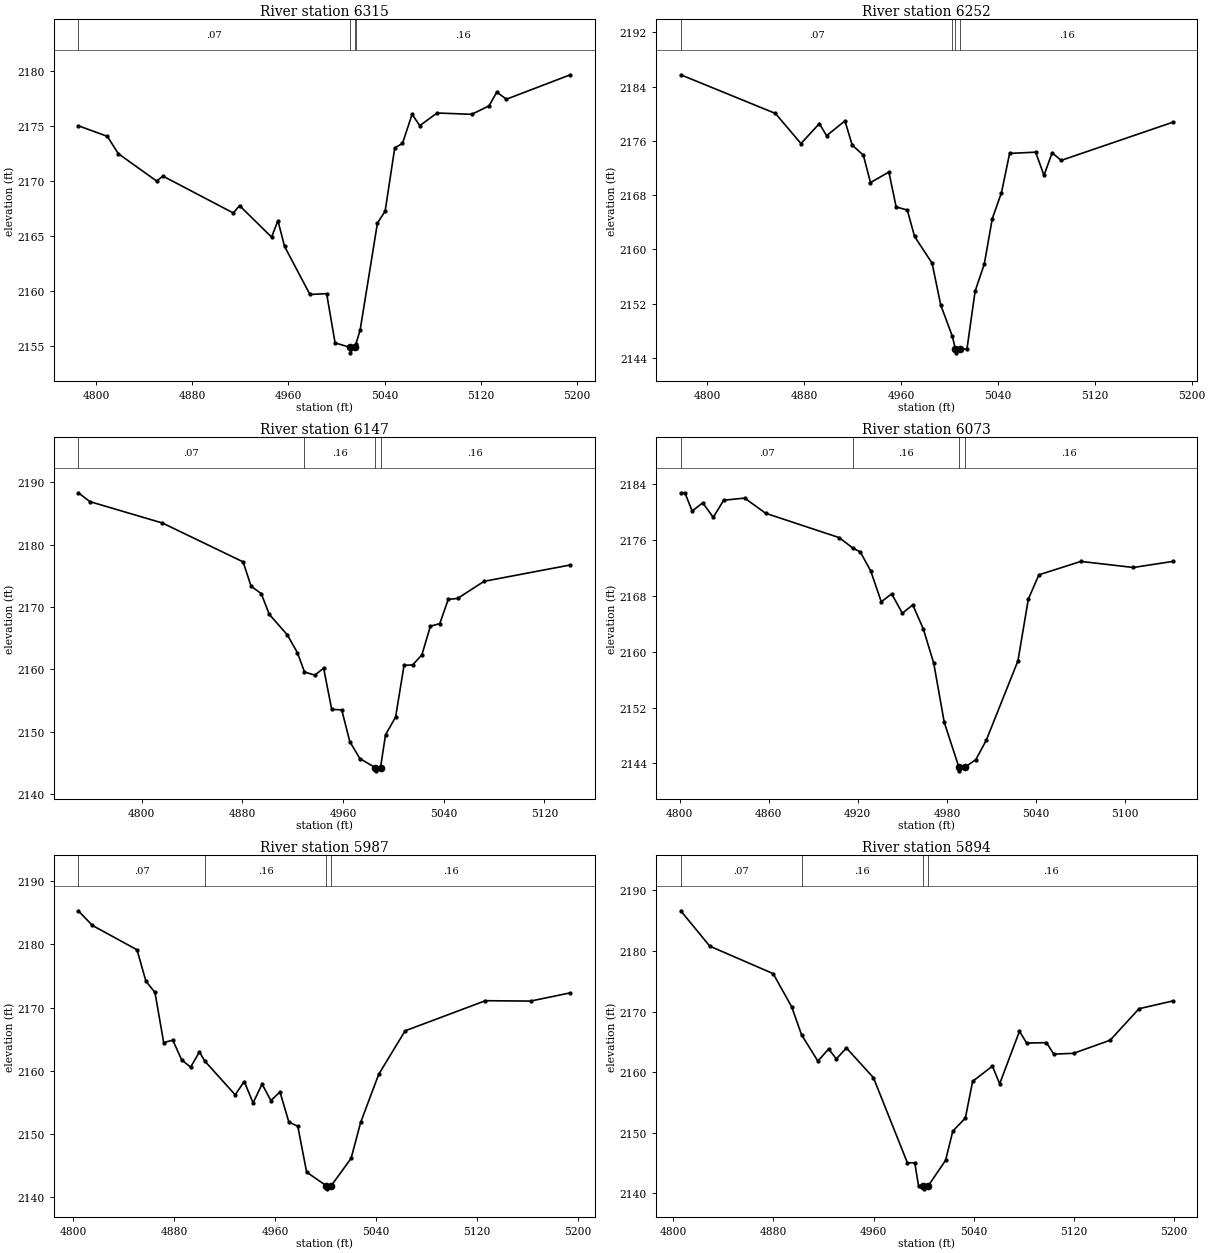
Type RM Length L Ch R = 1 ,6315    ,63,63,63
BEGIN DESCRIPTION:
Elm 01 21 6315.16
END DESCRIPTION:
XS GIS Cut Line= 3
      1513012.09      6804514.53      1513208.22      6804450.31
      1513366.19      6804323.58
#Sta/Elev= 30
  4785.4 2175.04  4809.5 2174.08  4818.6 2172.51  4850.5 2170.02  4855.7 2170.47
  4914.2 2167.12  4919.4 2167.79    4946 2164.93  4951.3 2166.42  4956.8 2164.09
  4977.9 2159.72  4991.8 2159.79  4998.8 2155.32  5011.2 2154.92  5011.4 2154.42
  5015.2 2154.92    5016  2155.2  5019.6 2156.47    5034  2166.2  5040.4 2167.28
  5048.4 2173.04  5054.8 2173.43  5062.8 2176.08  5069.2 2175.05  5083.6  2176.2
  5112.4 2176.08  5126.8 2176.85  5133.2  2178.1  5141.2 2177.45  5194.3 2179.67
#Mann= 4 ,-1 , 0
  4785.4     .07       0  5011.2     .07       0  5015.2     .07       0
    5016     .16       0
Bank Sta=5011.2,5015.2
XS Rating Curve= 0 ,0
Exp/Cntr=0.3,0.1

Type RM Length L Ch R = 1 ,6252    ,105,105,105
BEGIN DESCRIPTION:
Elm 01 21 6252.09
END DESCRIPTION:
XS GIS Cut Line= 3
      1513076.25      6804606.57      1513251.62      6804493.71
       1513399.8      6804362.76
#Sta/Elev= 30
    4778 2185.73  4856.2 2180.03  4877.3 2175.59  4892.5 2178.54  4898.4 2176.75
  4913.6 2178.93  4919.6 2175.37  4928.8 2173.88  4934.7 2169.84  4949.9 2171.39
  4955.9 2166.25  4965.1 2165.79  4971.1  2161.9  4985.6 2157.95  4992.7  2151.8
  5002.3 2147.18  5004.9 2145.24  5005.1 2144.74  5008.9 2145.24  5014.4 2145.33
  5021.1 2153.83  5028.7 2157.83  5035.3 2164.53  5042.9 2168.36  5049.6 2174.14
  5071.1 2174.32    5078  2170.9  5084.7 2174.23  5092.2 2173.11  5184.3 2178.73
#Mann= 4 ,-1 , 0
    4778     .07       0  5002.3     .16       0  5004.9     .07       0
  5008.9     .16       0
Bank Sta=5004.9,5008.9
XS Rating Curve= 0 ,0
Exp/Cntr=0.3,0.1

Type RM Length L Ch R = 1 ,6147    ,74,74,74
BEGIN DESCRIPTION:
Elm 01 21 6147.37
END DESCRIPTION:
XS GIS Cut Line= 3
       1513168.3      6804655.16      1513359.26      6804502.39
      1513468.64      6804405.16
#Sta/Elev= 30
  4749.7  2188.3  4758.9 2186.88  4816.5 2183.45  4880.6 2177.22    4887  2173.3
    4895 2172.14  4901.4 2168.81  4915.8  2165.5  4923.8 2162.64  4929.4 2159.56
  4937.6 2159.05  4944.6 2160.17    4951 2153.57    4959 2153.47  4965.4 2148.39
  4973.4 2145.67  4985.8  2144.2  4986.1  2143.7  4989.8  2144.2  4993.8 2149.49
  5001.8 2152.33  5008.5 2160.62  5015.3 2160.69  5022.7 2162.31  5029.4 2166.89
  5036.9 2167.32  5043.6 2171.19  5051.1 2171.36  5072.1  2174.1  5140.6 2176.72
#Mann= 4 ,-1 , 0
  4749.7     .07       0  4929.4     .16       0  4985.8     .07       0
  4989.8     .16       0
Bank Sta=4985.8,4989.8
XS Rating Curve= 0 ,0
Exp/Cntr=0.3,0.1

Type RM Length L Ch R = 1 ,6073    ,86,86,86
BEGIN DESCRIPTION:
Elm 01 21 6072.81
END DESCRIPTION:
XS GIS Cut Line= 3
      1513275.95      6804689.87      1513411.34      6804556.21
      1513510.14      6804455.68
#Sta/Elev= 30
  4800.8  2182.8  4803.6  2182.8  4808.5 2180.18  4815.6 2181.36  4822.7 2179.28
  4829.7 2181.73  4843.8 2182.04    4858 2179.86  4907.5 2176.37  4916.5  2174.9
  4921.7 2174.31  4928.7 2171.59  4935.8 2167.17  4942.8 2168.31    4950 2165.53
    4957 2166.73  4964.1 2163.28  4971.1 2158.39  4978.2 2149.89  4988.1 2143.44
  4988.4 2142.94  4992.1 2143.44  4999.5 2144.56  5006.5 2147.33  5027.8  2158.7
  5034.8 2167.55  5041.9 2171.04  5070.2 2172.96  5105.5 2172.09    5132 2172.96
#Mann= 4 ,-1 , 0
  4800.8     .07       0  4916.5     .16       0  4988.1     .07       0
  4992.1     .16       0
Bank Sta=4988.1,4992.1
XS Rating Curve= 0 ,0
Exp/Cntr=0.3,0.1

Type RM Length L Ch R = 1 ,5987    ,93,93,93
BEGIN DESCRIPTION:
Elm 01 21 5986.84
END DESCRIPTION:
XS GIS Cut Line= 3
      1513338.44      6804747.17      1513480.79       6804608.3
      1513605.77      6804464.22
#Sta/Elev= 30
  4804.3  2185.3  4815.4 2182.99  4850.8 2179.13  4857.8 2174.18    4865 2172.39
  4871.9 2164.47  4879.1 2164.85  4886.1 2161.76  4893.2 2160.58  4900.2 2162.99
  4904.5 2161.54  4928.5 2156.22  4935.7 2158.32  4942.7 2154.93  4949.8 2157.91
  4956.8 2155.31    4964 2156.67    4971 2151.92  4978.1 2151.24  4985.1    2144
  5000.6 2141.86  5000.9 2141.36  5004.6 2141.86  5020.3 2146.17  5027.9 2151.87
  5042.2 2159.47  5063.1 2166.33  5126.7 2171.09  5162.4 2171.03  5193.9 2172.33
#Mann= 4 ,-1 , 0
  4804.3     .07       0  4904.5     .16       0  5000.6     .07       0
  5004.6     .16       0
Bank Sta=5000.6,5004.6
XS Rating Curve= 0 ,0
Exp/Cntr=0.3,0.1

Type RM Length L Ch R = 1 ,5894    ,115,115,115
BEGIN DESCRIPTION:
Elm 01 21 5893.72
END DESCRIPTION:
XS GIS Cut Line= 3
      1513449.56      6804806.18      1513557.18      6804653.43
      1513659.59      6804474.64
#Sta/Elev= 30
    4806 2186.63  4829.2 2180.79  4879.8 2176.26  4894.6 2170.79  4902.5 2166.16
  4915.5 2161.83  4924.1 2163.82  4930.3 2162.19  4938.3    2164  4959.9 2159.09
    4987 2145.05  4992.9 2145.05  4995.9 2141.25  4999.7 2141.25    5000 2140.75
  5003.7 2141.25  5017.5 2145.46  5023.3 2150.28  5033.3 2152.43  5039.1 2158.48
  5054.9    2161  5060.7 2158.08  5076.5 2166.74  5082.3  2164.8  5098.1 2164.87
  5103.9 2162.98  5119.7 2163.11  5148.9 2165.27    5172 2170.47  5198.9 2171.75
#Mann= 4 ,-1 , 0
    4806     .07       0  4902.5     .16       0  4999.7     .07       0
  5003.7     .16       0
Bank Sta=4999.7,5003.7
XS Rating Curve= 0 ,0
Exp/Cntr=0.3,0.1

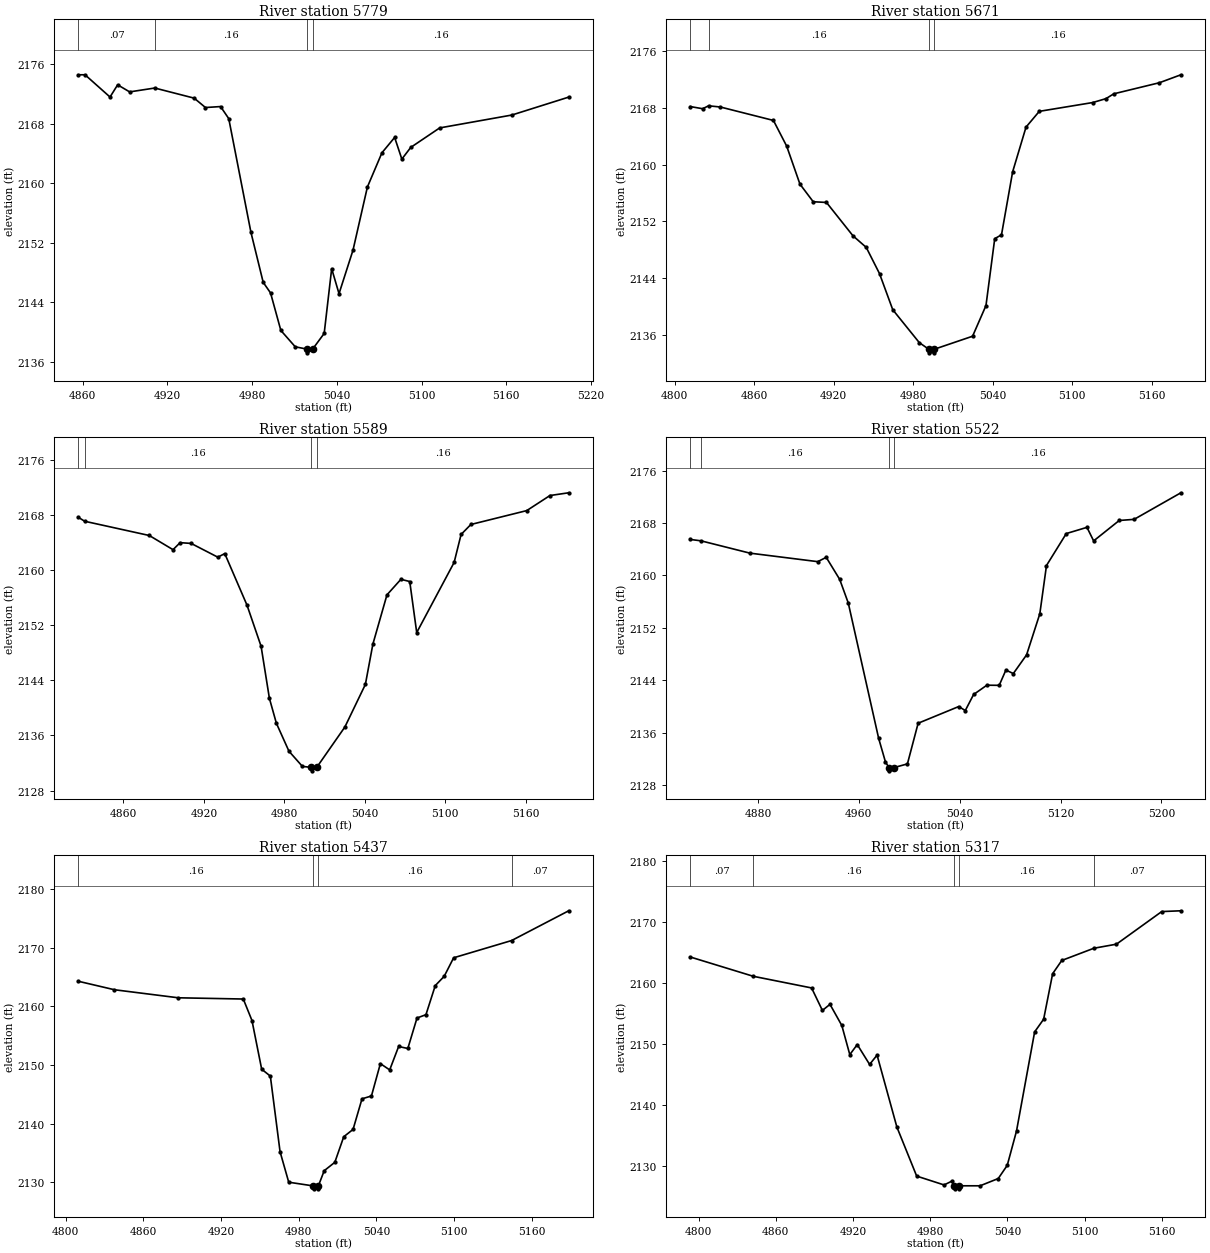
Type RM Length L Ch R = 1 ,5779    ,108,108,108
BEGIN DESCRIPTION:
Elm 01 21 5778.51
END DESCRIPTION:
XS GIS Cut Line= 3
      1513610.98      6804821.88      1513661.34      6804693.36
      1513704.74      6804488.54
#Sta/Elev= 30
  4856.8 2174.55  4861.6 2174.55  4879.3 2171.56  4884.7  2173.2  4893.2 2172.25
    4911 2172.77  4938.9 2171.41  4946.9 2170.15  4957.6 2170.28  4963.4 2168.66
  4979.1 2153.39  4987.8 2146.66    4993 2145.24  5000.3  2140.2  5010.5    2138
  5018.8 2137.69    5019 2137.19  5022.8 2137.69    5031  2139.8  5036.3  2148.5
  5041.5 2145.14  5051.4 2150.98  5061.6 2159.47  5071.9 2164.07  5080.9 2166.13
    5086 2163.22  5092.3 2164.79  5112.8 2167.41  5163.9 2169.14  5204.2 2171.55
#Mann= 4 ,-1 , 0
  4856.8     .07       0    4911     .16       0  5018.8     .07       0
  5022.8     .16       0
Bank Sta=5018.8,5022.8
XS Rating Curve= 0 ,0
Exp/Cntr=0.3,0.1

Type RM Length L Ch R = 1 ,5671    ,82,82,82
BEGIN DESCRIPTION:
Elm 01 21 5670.82
END DESCRIPTION:
XS GIS Cut Line= 3
       1513760.3      6804830.56      1513755.09      6804644.75
      1513734.39       6804461.9
#Sta/Elev= 30
    4812 2168.18  4821.2 2167.88  4825.7 2168.29  4834.6 2168.12  4874.6 2166.23
  4884.6 2162.61  4894.6 2157.26  4904.6 2154.78  4914.6 2154.68  4934.6 2149.98
  4944.6 2148.35  4954.6 2144.66  4964.6 2139.57  4984.6 2134.94  4991.8    2134
    4992  2133.5  4995.5  2133.5  4995.8    2134  5024.8 2135.84  5034.9 2140.16
  5041.5 2149.58  5046.6 2150.12    5055 2158.99  5065.1 2165.29  5075.1 2167.51
  5115.4 2168.75  5125.4  2169.3  5131.3 2169.98  5165.7 2171.54  5181.9 2172.66
#Mann= 4 ,-1 , 0
    4812     .07       0  4825.7     .16       0  4991.8     .07       0
  4995.8     .16       0
Bank Sta=4991.8,4995.8
XS Rating Curve= 0 ,0
Exp/Cntr=0.3,0.1

Type RM Length L Ch R = 1 ,5589    ,67,67,67
BEGIN DESCRIPTION:
Elm 01 21 5588.65
END DESCRIPTION:
XS GIS Cut Line= 3
      1513779.39       6804828.8      1513828.01      6804663.85
      1513883.58      6804478.05
#Sta/Elev= 30
  4826.3 2167.72  4831.1 2167.14  4879.3 2165.07    4897 2163.01  4902.3 2164.03
  4910.5 2163.92  4930.4 2161.92  4935.6 2162.44  4952.2 2154.94  4962.7 2148.97
  4968.9  2141.4  4974.1 2137.78  4983.5 2133.71  4993.5 2131.51  5000.2 2131.36
  5000.4 2130.86  5004.2 2131.36  5025.2 2137.23  5040.5 2143.42  5046.1 2149.28
  5056.6 2156.44    5067  2158.7  5073.6 2158.38  5078.8 2150.96  5106.7 2161.15
  5111.9 2165.22  5119.2 2166.67  5160.9 2168.69  5178.2 2170.88  5192.2 2171.28
#Mann= 4 ,-1 , 0
  4826.3     .07       0  4831.1     .16       0  5000.2     .07       0
  5004.2     .16       0
Bank Sta=5000.2,5004.2
XS Rating Curve= 0 ,0
Exp/Cntr=0.3,0.1

Type RM Length L Ch R = 1 ,5522    ,85,85,85
BEGIN DESCRIPTION:
Elm 01 21 5522.47
END DESCRIPTION:
XS GIS Cut Line= 3
       1513822.8      6804847.89      1513883.57      6804696.84
       1513952.5      6804481.42
#Sta/Elev= 30
  4826.4  2165.5  4834.8 2165.29  4873.6 2163.41  4927.4 2162.11  4934.1 2162.77
  4944.8  2159.4  4951.6 2155.79  4975.7 2135.11  4981.1 2131.51  4983.9 2130.66
  4984.1 2130.16  4987.9 2130.66  4998.5 2131.22    5007 2137.43  5039.2 2139.98
  5044.4 2139.37    5051 2141.82  5061.5 2143.24  5071.3 2143.22  5076.6 2145.55
  5082.5 2145.02    5093 2147.87  5103.5 2154.14  5108.8 2161.52  5124.5  2166.4
  5140.9 2167.35  5146.2 2165.28  5166.5  2168.4  5178.3 2168.57  5215.4 2172.63
#Mann= 4 ,-1 , 0
  4826.4     .07       0  4834.8     .16       0  4983.9     .07       0
  4987.9     .16       0
Bank Sta=4983.9,4987.9
XS Rating Curve= 0 ,0
Exp/Cntr=0.3,0.1

Type RM Length L Ch R = 1 ,5437    ,120,120,120
BEGIN DESCRIPTION:
Elm 01 21 5436.97
END DESCRIPTION:
XS GIS Cut Line= 3
      1513841.87      6804844.44      1513968.64      6804702.05
      1514105.16      6804572.43
#Sta/Elev= 30
  4809.6 2164.26  4837.6 2162.81  4886.9 2161.44  4937.1 2161.23  4943.8 2157.57
  4951.3 2149.27    4958 2148.09  4965.5 2135.21  4972.2 2130.01  4991.1 2129.38
  4991.4 2128.88  4994.9 2128.88  4995.1 2129.38  4999.6 2131.97  5007.8  2133.4
  5014.7 2137.76  5021.9 2139.01  5028.8 2144.22  5036.1 2144.71    5043 2150.22
  5050.2 2149.15  5057.1 2153.14  5064.2  2152.8  5071.3    2158  5078.2 2158.56
  5085.4 2163.52  5092.3  2165.1  5099.6 2168.26  5144.4  2171.2  5188.5 2176.27
#Mann= 4 ,-1 , 0
  4809.6     .16       0  4991.1     .07       0  4995.1     .16       0
  5144.4     .07       0
Bank Sta=4991.1,4995.1
XS Rating Curve= 0 ,0
Exp/Cntr=0.3,0.1

Type RM Length L Ch R = 1 ,5317    ,94,94,94
BEGIN DESCRIPTION:
Elm 01 21 5316.56
END DESCRIPTION:
XS GIS Cut Line= 3
      1513874.86      6804898.24      1514051.97      6804788.85
      1514176.97      6804669.06
#Sta/Elev= 30
  4793.6 2164.24  4842.5 2161.08  4887.8 2159.17  4896.2 2155.48  4902.1 2156.48
  4911.3 2153.01  4917.5 2148.23  4923.3 2149.88  4932.9 2146.62  4938.7 2148.15
  4954.1 2136.35  4969.5  2128.3  4990.8 2126.85  4996.7 2127.46  4998.6 2126.71
  4998.9 2126.21  5002.4 2126.21  5002.6 2126.71  5018.8 2126.71  5032.9  2127.9
  5039.9 2130.06  5047.1 2135.69  5061.2 2151.96  5068.2 2154.04  5075.2 2161.51
  5082.3 2163.68  5107.2 2165.68  5124.8 2166.35    5160  2171.7  5174.9 2171.83
#Mann= 5 ,-1 , 0
  4793.6     .07       0  4842.5     .16       0  4998.6     .07       0
  5002.6     .16       0  5107.2     .07       0
Bank Sta=4998.6,5002.6
XS Rating Curve= 0 ,0
Exp/Cntr=0.3,0.1

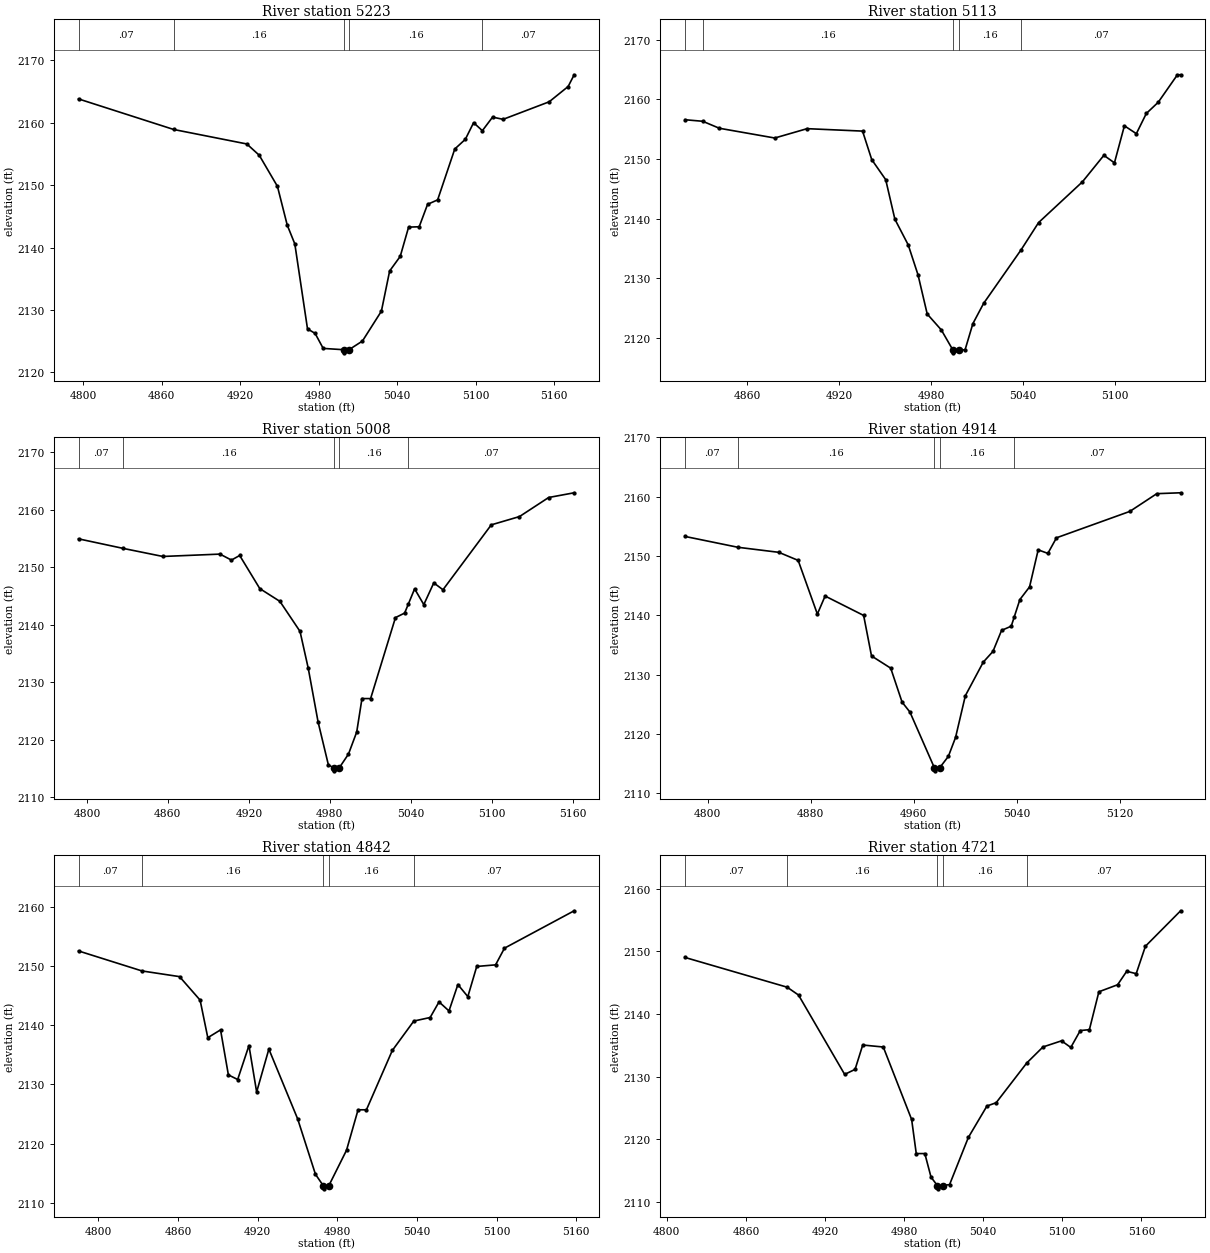
Type RM Length L Ch R = 1 ,5223    ,110,110,110
BEGIN DESCRIPTION:
Elm 01 21 5222.7
END DESCRIPTION:
XS GIS Cut Line= 3
      1513914.81      6804976.35      1514090.16      6804870.45
      1514227.16      6804762.93
#Sta/Elev= 30
  4796.4 2163.84  4869.2 2158.94  4925.1 2156.62  4934.6 2154.81  4948.5 2149.83
    4956 2143.61  4961.8  2140.6  4971.5 2126.98  4977.3 2126.26  4983.5 2123.85
  4999.2 2123.64  4999.4 2123.14  5003.2 2123.64  5013.5 2125.03    5028 2129.82
  5034.3 2136.26  5042.4  2138.6  5048.8 2143.29  5056.9 2143.35  5063.3 2146.94
    5071 2147.66  5084.1 2155.81  5092.2 2157.37  5098.5 2160.03  5105.2 2158.75
    5113 2160.92  5121.1 2160.57  5156.3 2163.38  5170.8 2165.83  5175.4 2167.71
#Mann= 5 ,-1 , 0
  4796.4     .07       0  4869.2     .16       0  4999.2     .07       0
  5003.2     .16       0  5105.2     .07       0
Bank Sta=4999.2,5003.2
XS Rating Curve= 0 ,0
Exp/Cntr=0.3,0.1

Type RM Length L Ch R = 1 ,5113    ,105,105,105
BEGIN DESCRIPTION:
Elm 01 21 5113.39
END DESCRIPTION:
XS GIS Cut Line= 3
       1514032.9      6805016.26      1514182.18      6804919.06
      1514293.28      6804825.32
#Sta/Elev= 30
  4819.4  2156.6    4831 2156.34  4841.8 2155.17    4878 2153.53  4899.1  2155.1
  4935.3 2154.69  4941.3  2149.9  4950.4 2146.54  4956.4 2139.89  4965.1 2135.58
  4971.5 2130.55  4977.5 2123.97  4986.7  2121.3  4994.2 2117.95  4994.5 2117.45
  4998.2 2117.95  5002.2 2117.95  5007.3 2122.35  5014.3 2125.75  5038.9  2134.8
  5050.2 2139.33  5078.8 2146.17  5092.8 2150.62  5099.7 2149.36  5106.2 2155.58
    5114 2154.26  5120.5 2157.65  5128.3 2159.54  5140.8 2164.15  5142.9 2164.15
#Mann= 5 ,-1 , 0
  4819.4     .07       0    4831     .16       0  4994.2     .07       0
  4998.2     .16       0  5038.9     .07       0
Bank Sta=4994.2,4998.2
XS Rating Curve= 0 ,0
Exp/Cntr=0.3,0.1

Type RM Length L Ch R = 1 ,5008    ,94,94,94
BEGIN DESCRIPTION:
Elm 01 21 5007.93
END DESCRIPTION:
XS GIS Cut Line= 3
      1514088.45      6805108.28      1514263.77       6804988.5
      1514378.37      6804884.33
#Sta/Elev= 30
  4793.8 2154.92  4826.9 2153.26  4856.3 2151.86  4898.6 2152.27  4907.1 2151.23
  4913.2 2152.03  4928.1 2146.28    4943 2144.06  4957.9 2138.85    4964 2132.44
  4971.3  2123.1  4978.9 2115.68  4982.9 2115.13  4983.2 2114.63  4986.9 2115.13
  4993.8 2117.54  4999.9 2121.37  5003.8 2127.18  5010.2 2127.18  5028.6 2141.24
  5035.4 2142.03  5038.2 2143.62  5042.8 2146.24  5049.6  2143.5    5057 2147.27
  5063.8 2146.08  5099.6 2157.35  5120.5 2158.79  5142.1  2162.1    5161 2162.92
#Mann= 5 ,-1 , 0
  4793.8     .07       0  4826.9     .16       0  4982.9     .07       0
  4986.9     .16       0  5038.2     .07       0
Bank Sta=4982.9,4986.9
XS Rating Curve= 0 ,0
Exp/Cntr=0.3,0.1

Type RM Length L Ch R = 1 ,4914    ,72,72,72
BEGIN DESCRIPTION:
Elm 01 21 4914.3
END DESCRIPTION:
XS GIS Cut Line= 3
      1514145.74       6805181.2      1514319.33      6805063.16
      1514449.53      6804946.85
#Sta/Elev= 30
  4782.5 2153.29  4823.6 2151.46  4855.3 2150.61  4870.3 2149.25  4885.2  2140.2
  4891.2 2143.24  4921.1 2139.97  4927.2 2133.14  4942.1 2131.08  4950.9 2125.36
    4957 2123.68    4976 2114.27  4976.3 2113.77    4980 2114.27  4986.8  2116.2
  4992.4  2119.4    5000 2126.44  5013.9  2132.1  5021.4  2133.9  5028.1 2137.45
  5035.6 2138.16  5037.8 2139.63  5042.3 2142.65  5049.8 2144.78  5056.5 2151.03
    5064 2150.43  5070.7 2153.06  5127.6 2157.51  5148.5  2160.5    5167 2160.65
#Mann= 5 ,-1 , 0
  4782.5     .07       0  4823.6     .16       0    4976     .07       0
    4980     .16       0  5037.8     .07       0
Bank Sta=4976,4980
XS Rating Curve= 0 ,0
Exp/Cntr=0.3,0.1

Type RM Length L Ch R = 1 ,4842    ,121,121,121
BEGIN DESCRIPTION:
Elm 01 21 4842.21
END DESCRIPTION:
XS GIS Cut Line= 3
      1514192.59      6805221.15      1514374.89      6805110.03
      1514494.69      6805004.12
#Sta/Elev= 30
    4785 2152.55  4832.8 2149.17  4861.1 2148.21  4876.6 2144.24  4882.4 2137.89
    4892 2139.21  4897.9  2131.6  4904.9 2130.82  4913.4 2136.56  4919.2 2128.71
  4928.4 2135.96  4950.1 2124.16  4963.5  2114.8  4969.5 2112.84  4969.7 2112.34
  4973.5 2112.84  4986.9 2118.86  4995.6  2125.7  5001.9  2125.7  5021.4 2135.73
  5037.6  2140.7  5049.9  2141.3  5056.6 2143.94  5064.1 2142.41  5070.8 2146.87
  5078.3 2144.83    5085 2149.93  5099.2  2150.2  5105.9 2153.02  5158.4 2159.34
#Mann= 5 ,-1 , 0
    4785     .07       0  4832.8     .16       0  4969.5     .07       0
  4973.5     .16       0  5037.6     .07       0
Bank Sta=4969.5,4973.5
XS Rating Curve= 0 ,0
Exp/Cntr=0.3,0.1

Type RM Length L Ch R = 1 ,4721    ,60,60,60
BEGIN DESCRIPTION:
Elm 01 21 4721.41
END DESCRIPTION:
XS GIS Cut Line= 3
      1514270.74      6805309.67       1514423.5      6805219.41
      1514561.23      6805076.51
#Sta/Elev= 30
  4813.8 2149.03  4891.3 2144.28  4899.9 2143.03  4934.9 2130.36  4942.8 2131.16
  4948.6 2135.05  4964.2 2134.73  4985.7 2123.16  4989.2 2117.72  4995.7 2117.72
  5000.4 2113.96  5005.3 2112.59  5005.6 2112.09  5009.3 2112.59  5014.5 2112.78
  5028.7 2120.29  5042.8 2125.31  5049.8 2125.84    5073 2132.18  5085.3 2134.74
  5099.4 2135.72  5106.4 2134.66  5113.6 2137.36  5120.5  2137.5  5127.7 2143.55
  5141.9 2144.67  5148.8 2146.82    5156 2146.44    5163 2150.82  5189.7 2156.48
#Mann= 5 ,-1 , 0
  4813.8     .07       0  4891.3     .16       0  5005.3     .07       0
  5009.3     .16       0    5073     .07       0
Bank Sta=5005.3,5009.3
XS Rating Curve= 0 ,0
Exp/Cntr=0.3,0.1

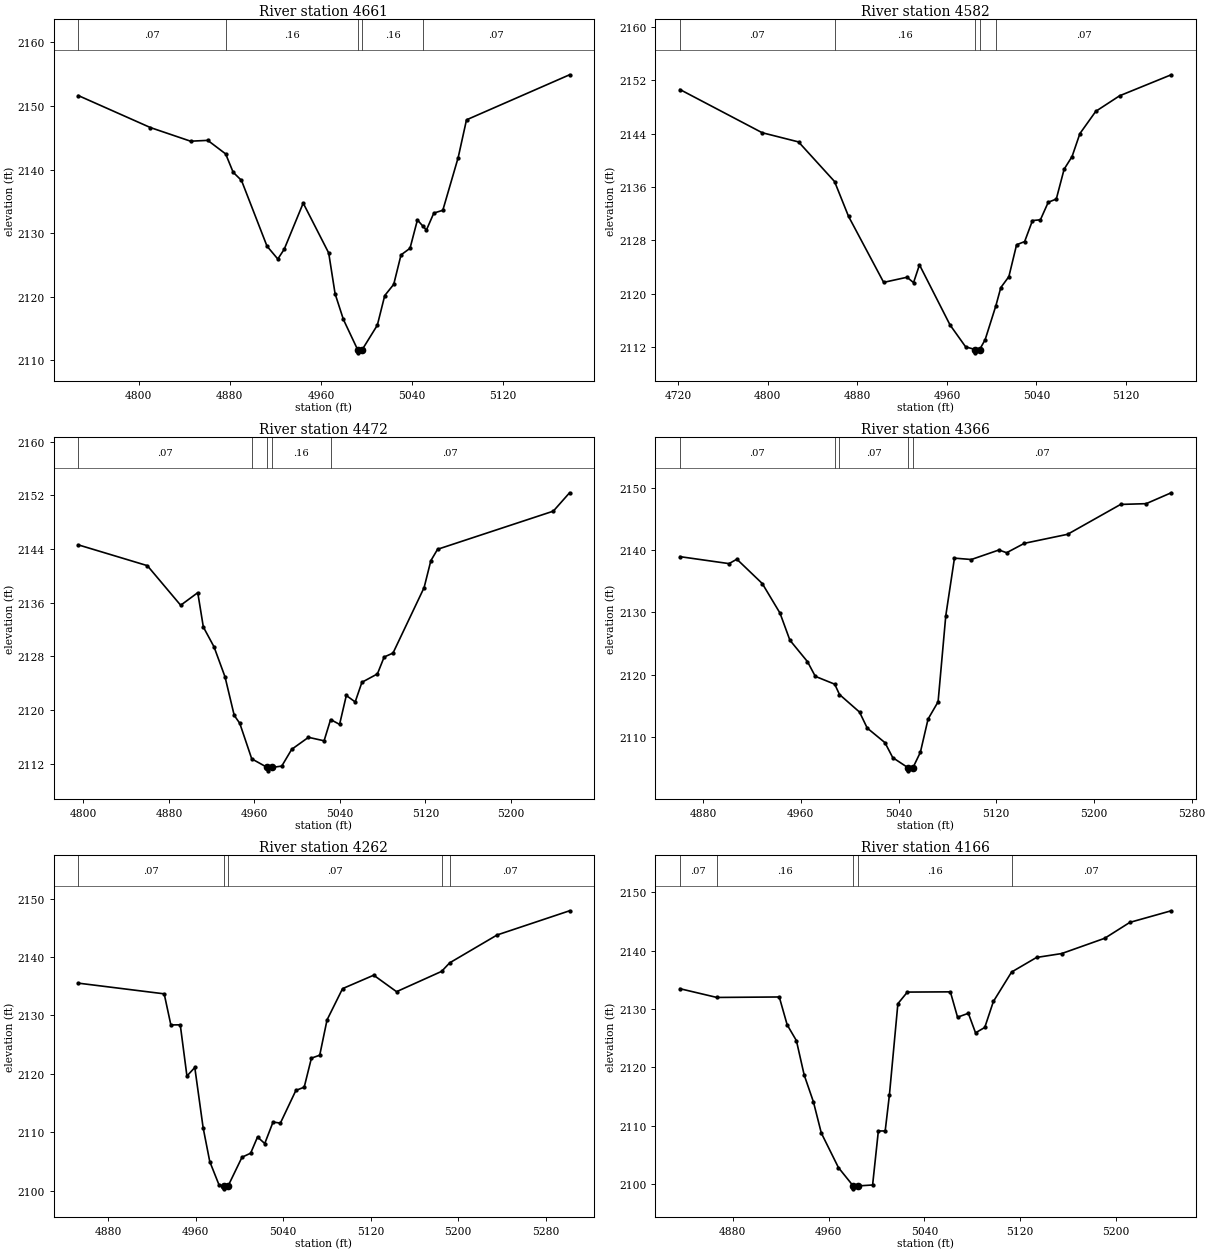
Type RM Length L Ch R = 1 ,4661    ,79,79,79
BEGIN DESCRIPTION:
Elm 01 21 4660.57
END DESCRIPTION:
XS GIS Cut Line= 3
      1514256.82      6805353.09      1514479.05      6805241.98
      1514620.71      6805126.23
#Sta/Elev= 30
  4746.9 2151.65  4810.3 2146.61  4845.5 2144.47  4860.6  2144.6  4876.3 2142.47
  4882.9 2139.58  4890.2  2138.3  4912.6 2127.96  4922.1 2125.93  4927.7 2127.46
  4944.4 2134.73  4966.8 2126.88  4972.4 2120.47  4979.7 2116.42  4992.2 2111.67
  4992.5 2111.17  4996.2 2111.67  5009.5 2115.52    5016 2120.18  5023.9 2121.95
  5030.3 2126.58  5038.2 2127.62  5044.7 2132.08  5049.4 2131.13  5052.6 2130.49
  5059.1 2133.16    5067  2133.6  5080.5  2141.9  5087.8 2147.83  5178.3 2154.92
#Mann= 5 ,-1 , 0
  4746.9     .07       0  4876.3     .16       0  4992.2     .07       0
  4996.2     .16       0  5049.4     .07       0
Bank Sta=4992.2,4996.2
XS Rating Curve= 0 ,0
Exp/Cntr=0.3,0.1

Type RM Length L Ch R = 1 ,4582    ,110,110,110
BEGIN DESCRIPTION:
Elm 01 21 4581.58
END DESCRIPTION:
XS GIS Cut Line= 3
      1514281.15      6805365.23      1514543.29      6805283.64
       1514657.9      6805165.56
#Sta/Elev= 30
  4721.4  2150.6  4794.9 2144.12  4827.4 2142.74  4859.6  2136.8  4872.1 2131.57
  4903.5 2121.67  4924.4 2122.44  4930.2 2121.63  4935.5  2124.3  4962.8 2115.29
  4976.8 2111.99  4985.3  2111.6  4985.5  2111.1  4989.3  2111.6  4994.2 2113.07
  5003.8 2118.17  5008.2 2120.89  5015.4 2122.53  5022.3 2127.31  5029.5 2127.79
  5036.5 2130.94  5043.6 2131.06  5050.6 2133.69  5057.8 2134.17  5064.8 2138.65
  5071.9 2140.55  5078.9 2143.99  5093.1 2147.33  5114.4 2149.66  5160.5 2152.81
#Mann= 5 ,-1 , 0
  4721.4     .07       0  4859.6     .16       0  4985.3     .07       0
  4989.3     .16       0  5003.8     .07       0
Bank Sta=4985.3,4989.3
XS Rating Curve= 0 ,0
Exp/Cntr=0.3,0.1

Type RM Length L Ch R = 1 ,4472    ,106,106,106
BEGIN DESCRIPTION:
Elm 01 21 4471.87
END DESCRIPTION:
XS GIS Cut Line= 3
      1514362.77      6805443.36      1514560.65      6805387.81
      1514763.78      6805235.03
#Sta/Elev= 30
  4795.2 2144.62  4859.8 2141.52    4891 2135.61    4907 2137.49  4912.2 2132.37
  4922.2 2129.41  4932.5 2124.93  4941.1 2119.19  4946.3    2118  4957.5  2112.7
  4972.1 2111.41  4972.3 2110.91  4976.1 2111.41  4985.6 2111.62  4994.9 2114.12
  5010.6 2115.91  5025.2 2115.39  5031.3 2118.56  5039.7 2117.84    5046 2122.15
  5054.3 2121.19  5060.6 2124.12  5075.1 2125.37  5081.4 2127.89  5089.7 2128.48
  5118.8 2138.25  5125.1 2142.26  5131.4 2143.96  5239.7 2149.65  5254.9 2152.39
#Mann= 5 ,-1 , 0
  4795.2     .07       0  4957.5     .16       0  4972.1     .07       0
  4976.1     .16       0  5031.3     .07       0
Bank Sta=4972.1,4976.1
XS Rating Curve= 0 ,0
Exp/Cntr=0.3,0.1

Type RM Length L Ch R = 1 ,4366    ,104,104,104
BEGIN DESCRIPTION:
Elm 01 21 4365.7
END DESCRIPTION:
XS GIS Cut Line= 3
      1514522.45      6805551.01      1514633.57       6805464.2
      1514793.26      6805257.64
#Sta/Elev= 30
  4861.1 2138.95  4901.3 2137.83  4907.7 2138.54  4928.5 2134.63    4943 2129.88
  4951.1 2125.53  4965.5 2122.08  4971.9 2119.72  4987.8 2118.46  4991.7  2116.8
  5008.1 2113.98  5014.4 2111.41  5028.9 2109.07  5035.3 2106.66  5047.8 2105.04
    5048 2104.54  5051.8 2105.04  5057.9 2107.52  5064.2 2112.86  5072.4 2115.63
  5078.7 2129.47  5085.8 2138.71  5099.6 2138.49  5122.2 2140.02  5128.5 2139.58
    5143 2141.09  5178.4 2142.54  5221.8 2147.34  5242.7 2147.46  5263.2 2149.21
#Mann= 5 ,-1 , 0
  4861.1     .07       0  4987.8     .16       0  4991.7     .07       0
  5047.8     .07       0  5051.8     .07       0
Bank Sta=5047.8,5051.8
XS Rating Curve= 0 ,0
Exp/Cntr=0.3,0.1

Type RM Length L Ch R = 1 ,4262    ,96,96,96
BEGIN DESCRIPTION:
Elm 01 21 4262.25
END DESCRIPTION:
XS GIS Cut Line= 3
      1514588.44      6805620.44      1514711.69      6805531.91
      1514907.88      6805307.94
#Sta/Elev= 30
  4852.5 2135.52  4931.1 2133.69  4937.2 2128.37  4945.8 2128.39  4951.9 2119.63
  4959.1 2121.09  4966.7 2110.81  4972.8 2104.99  4981.4 2100.94  4985.6 2100.83
  4985.8 2100.33  4989.6 2100.83  5002.3 2105.74  5010.2 2106.43  5016.5  2109.2
  5023.1 2108.08  5030.7 2111.76  5037.4 2111.57  5051.6 2117.17  5059.2 2117.72
  5065.8 2122.69  5073.4 2123.19  5080.1 2129.23  5094.3 2134.58  5122.8 2136.88
  5143.7 2134.06  5184.9 2137.53  5192.3 2138.99  5235.7 2143.76    5302  2147.9
#Mann= 5 ,-1 , 0
  4852.5     .07       0  4985.6     .07       0  4989.6     .07       0
  5184.9     .16       0  5192.3     .07       0
Bank Sta=4985.6,4989.6
XS Rating Curve= 0 ,0
Exp/Cntr=0.3,0.1

Type RM Length L Ch R = 1 ,4166    ,126,126,126
BEGIN DESCRIPTION:
Elm 01 21 4166.13
END DESCRIPTION:
XS GIS Cut Line= 3
      1514678.68      6805648.25      1514807.18      6805538.85
      1514942.59       6805339.2
#Sta/Elev= 30
    4836 2133.49  4866.8 2131.99  4918.9 2132.07  4925.5 2127.29  4933.2 2124.58
  4939.7 2118.68  4947.4 2114.08    4954 2108.72  4968.3 2102.79  4980.6 2099.65
  4980.8 2099.15  4984.6 2099.65  4996.8 2099.81  5001.6 2109.08  5007.3 2109.08
  5010.8  2115.2  5017.9 2130.92  5025.8 2132.91  5061.7 2132.95  5067.7  2128.6
  5076.7 2129.27  5082.7 2125.92  5090.4 2126.84  5097.6  2131.3  5112.8 2136.35
  5133.6 2138.85  5154.6 2139.52  5190.5 2142.14  5211.5 2144.87    5246 2146.86
#Mann= 5 ,-1 , 0
    4836     .07       0  4866.8     .16       0  4980.6     .07       0
  4984.6     .16       0  5112.8     .07       0
Bank Sta=4980.6,4984.6
XS Rating Curve= 0 ,0
Exp/Cntr=0.3,0.1