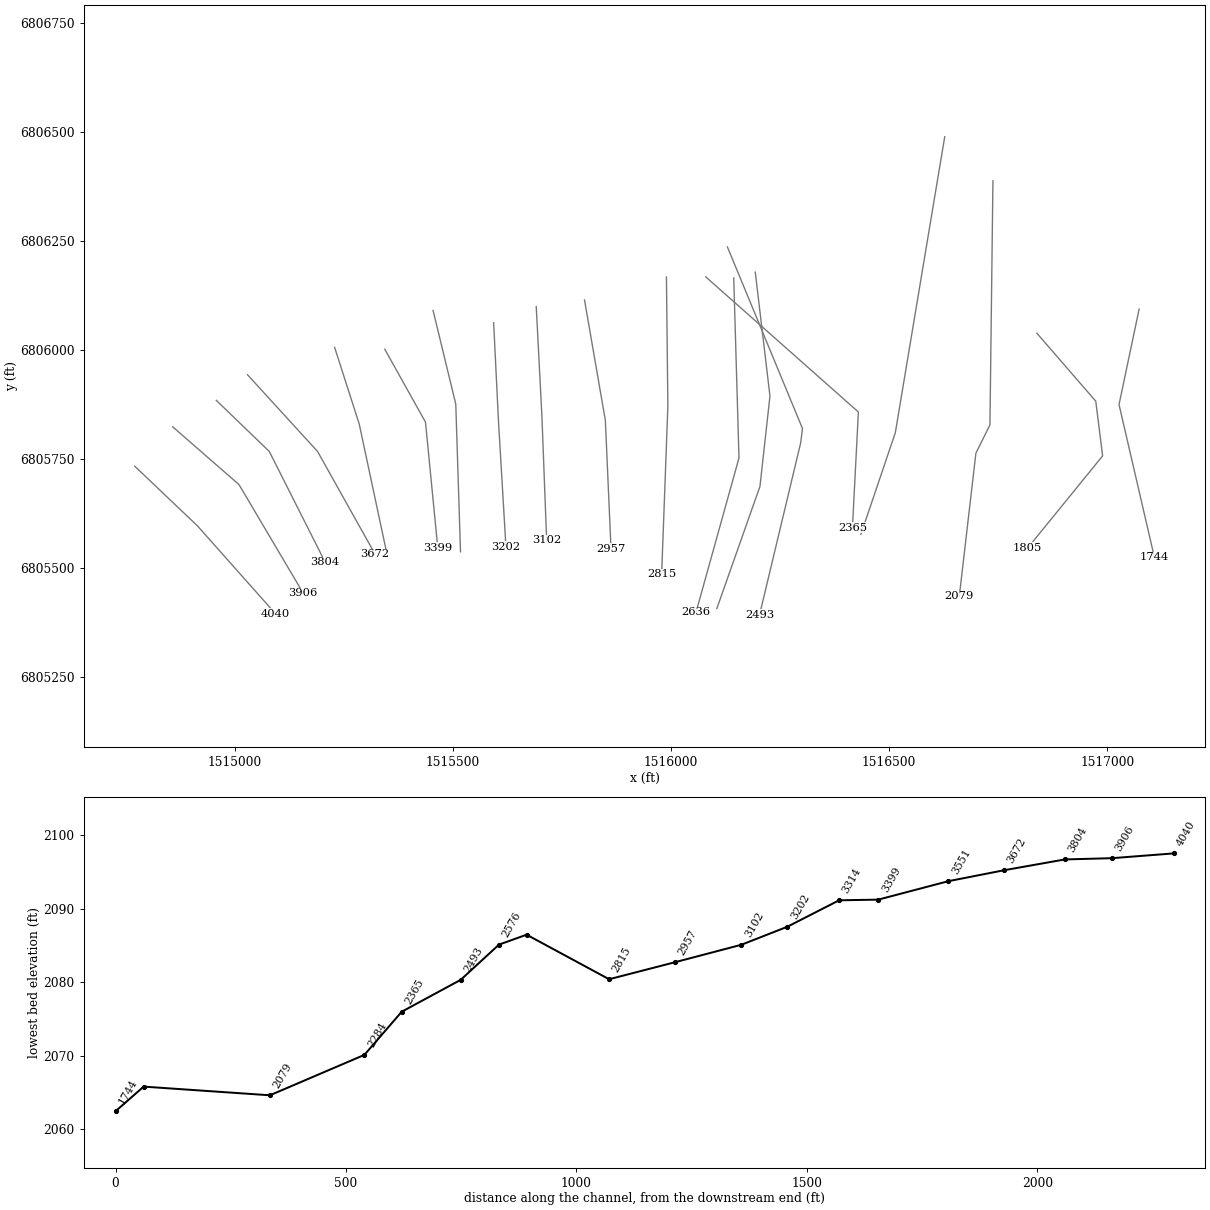
HEC-RAS study Elm 01 21.prj: Elm 01 21 Base Level Engineering

--- Elm 01 21.g01 (geometry) --- (continued)

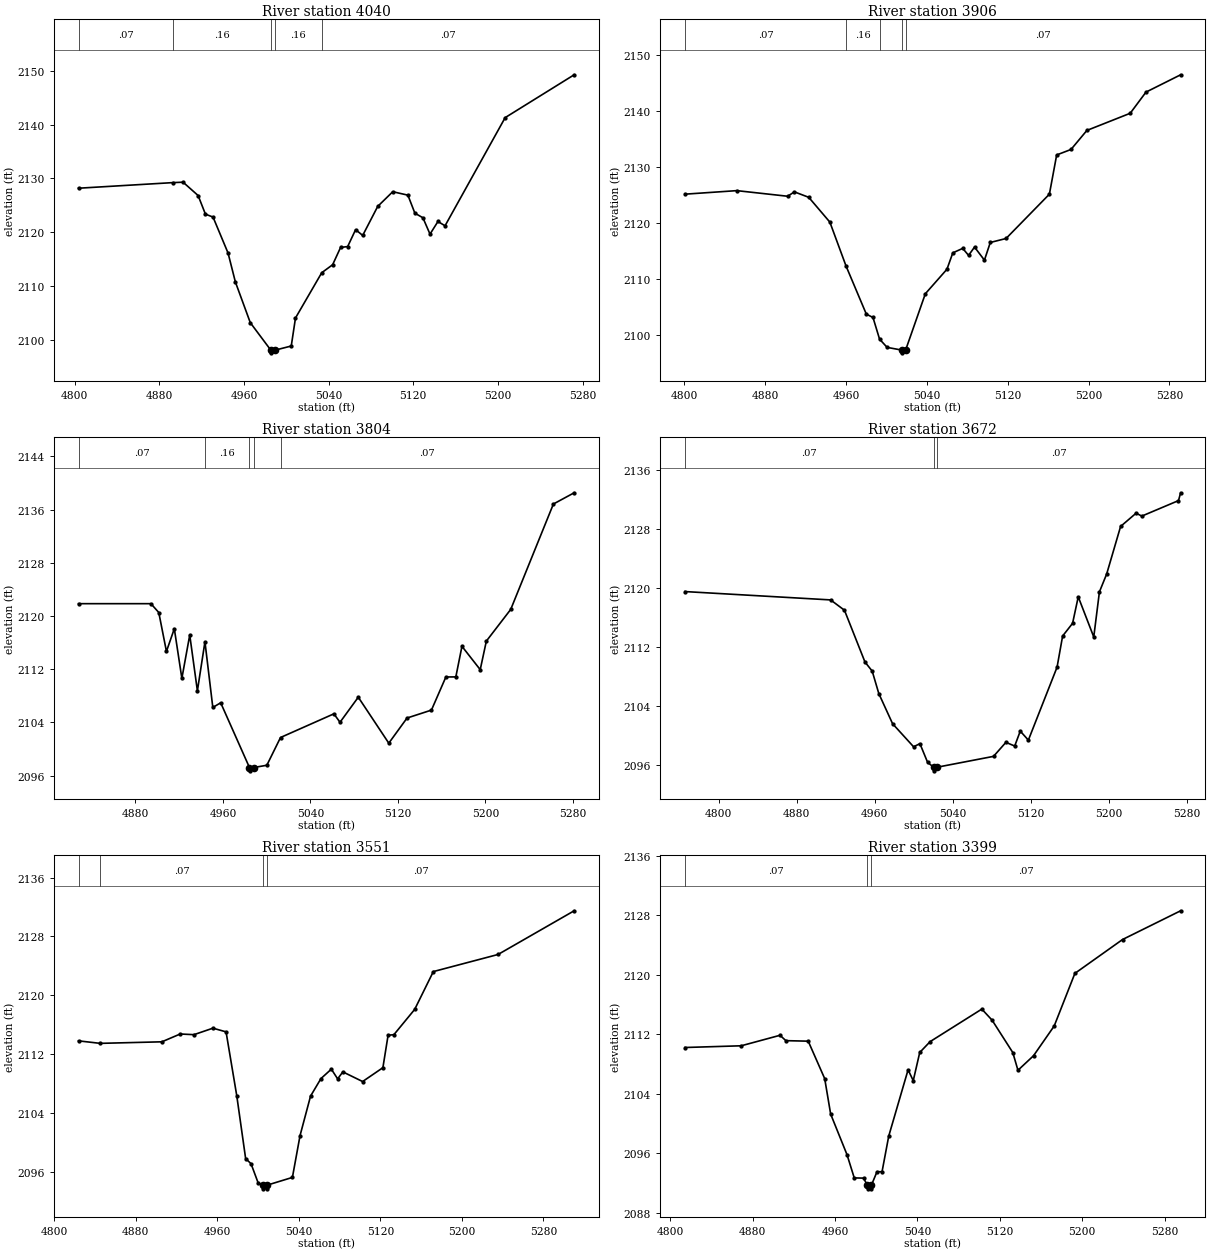
Type RM Length L Ch R = 1 ,4040    ,134,134,134
BEGIN DESCRIPTION:
Elm 01 21 4039.83
END DESCRIPTION:
XS GIS Cut Line= 3
      1514770.71       6805733.3      1514914.82      6805596.14
      1515093.66      6805394.73
#Sta/Elev= 30
  4803.7 2128.16  4892.7  2129.2  4902.5 2129.28  4916.7  2126.8  4923.6 2123.34
  4930.8 2122.79    4945  2116.1  4951.9 2110.73    4966 2103.15  4985.4 2098.04
  4985.7 2097.54  4989.4 2098.04  5004.7 2098.81  5008.7 2104.02  5033.5 2112.44
  5043.8 2113.93  5051.3 2117.14    5058 2117.31  5065.5 2120.45  5072.2 2119.38
  5086.4 2124.78  5100.6 2127.51  5114.9 2126.87  5121.5 2123.52  5129.1 2122.66
  5135.8 2119.62  5143.3 2121.97    5150 2121.17  5206.8 2141.29    5272 2149.26
#Mann= 5 ,-1 , 0
  4803.7     .07       0  4892.7     .16       0  4985.4     .07       0
  4989.4     .16       0  5033.5     .07       0
Bank Sta=4985.4,4989.4
XS Rating Curve= 0 ,0
Exp/Cntr=0.3,0.1

Type RM Length L Ch R = 1 ,3906    ,102,102,102
BEGIN DESCRIPTION:
Elm 01 21 3905.63
END DESCRIPTION:
XS GIS Cut Line= 3
      1514857.74      6805823.57      1515009.65      6805691.19
       1515156.8      6805442.34
#Sta/Elev= 30
  4800.5 2125.17  4851.8  2125.8  4902.1  2124.8  4908.8 2125.58    4923 2124.61
  4943.9 2120.19    4960 2112.33    4980 2103.79  4986.6 2103.19  4993.1 2099.33
  5000.6 2097.86  5014.9 2097.39  5015.2 2096.89  5018.9 2097.39  5038.4 2107.42
  5059.8 2111.79  5065.6 2114.71  5075.4 2115.51  5081.2 2114.26  5087.1 2115.74
  5096.9 2113.41  5102.7 2116.56  5118.3 2117.27  5161.2 2125.17  5168.4 2132.16
  5182.6 2133.14  5198.3 2136.53  5241.2 2139.59  5256.8 2143.36  5291.1 2146.45
#Mann= 5 ,-1 , 0
  4800.5     .07       0    4960     .16       0  4993.1     .07       0
  5014.9     .07       0  5018.9     .07       0
Bank Sta=5014.9,5018.9
XS Rating Curve= 0 ,0
Exp/Cntr=0.3,0.1

Type RM Length L Ch R = 1 ,3804    ,132,132,132
BEGIN DESCRIPTION:
Elm 01 21 3803.67
END DESCRIPTION:
XS GIS Cut Line= 3
      1514957.55      6805884.35       1515079.1      6805767.15
      1515207.13      6805513.26
#Sta/Elev= 30
    4828 2121.85  4894.2 2121.85  4901.4 2120.52  4908.4 2114.67  4915.6 2118.09
  4922.5 2110.62  4929.7 2117.14  4936.7 2108.75  4943.6 2116.12  4950.8 2106.25
    4958 2106.95  4984.3 2097.22  4984.6 2096.72  4988.3 2097.22  5000.2 2097.56
  5012.7 2101.73  5061.5 2105.29  5067.1 2104.02  5083.8 2107.79  5111.7 2100.88
  5128.4 2104.66  5150.7 2105.85  5163.9 2110.83    5173 2110.84  5178.6 2115.44
  5195.3 2111.93  5200.9 2116.22  5223.2 2120.99  5262.2 2136.83  5281.2 2138.52
#Mann= 5 ,-1 , 0
    4828     .07       0  4943.6     .16       0  4984.3     .07       0
  4988.3     .16       0  5012.7     .07       0
Bank Sta=4984.3,4988.3
XS Rating Curve= 0 ,0
Exp/Cntr=0.3,0.1

Type RM Length L Ch R = 1 ,3672    ,121,121,121
BEGIN DESCRIPTION:
Elm 01 21 3671.95
END DESCRIPTION:
XS GIS Cut Line= 3
      1515029.16      6805942.96      1515189.77      6805767.15
      1515321.47      6805531.83
#Sta/Elev= 30
  4765.6 2119.53  4914.8  2118.4    4929    2117    4950 2109.99  4957.4 2108.76
  4964.2 2105.71  4978.3 2101.63  4999.8 2098.51  5006.3 2098.93  5014.2 2096.39
  5020.3 2095.75  5020.6 2095.25  5024.3 2095.75  5081.7 2097.21  5094.4 2099.11
  5103.4 2098.61  5109.1 2100.63  5117.4 2099.41  5146.8 2109.29  5152.5 2113.51
  5162.7 2115.23  5168.5 2118.82  5184.4 2113.38  5190.2 2119.49  5197.6  2121.9
  5211.9 2128.35  5227.8 2130.15  5233.6 2129.75  5271.2 2131.85  5273.4 2132.91
#Mann= 3 ,-1 , 0
  4765.6     .07       0  5020.3     .07       0  5024.3     .07       0
Bank Sta=5020.3,5024.3
XS Rating Curve= 0 ,0
Exp/Cntr=0.3,0.1

Type RM Length L Ch R = 1 ,3551    ,152,152,152
BEGIN DESCRIPTION:
Elm 01 21 3550.62
END DESCRIPTION:
XS GIS Cut Line= 3
      1515228.83      6806005.89      1515285.26      6805830.08
      1515348.19      6805534.96
#Sta/Elev= 30
  4823.8 2113.84  4845.1  2113.5  4905.6 2113.71  4923.6 2114.77  4937.1 2114.68
  4955.7 2115.56  4968.6 2115.06  4979.1 2106.39  4987.8 2097.87  4993.1 2097.17
  5000.1 2094.56  5004.9 2094.26  5005.2 2093.76  5008.7 2093.76  5008.9 2094.26
  5033.7 2095.31  5041.2 2100.99  5051.5 2106.34  5061.7 2108.72  5071.9    2110
  5078.1 2108.68  5083.2 2109.63  5102.6 2108.32  5122.5  2110.2  5127.6  2114.6
  5133.3 2114.68  5153.7 2118.11    5172 2123.24  5235.5 2125.56  5310.2 2131.49
#Mann= 4 ,-1 , 0
  4823.8    .035       0  4845.1     .07       0  5004.9     .07       0
  5008.9     .07       0
Bank Sta=5004.9,5008.9
XS Rating Curve= 0 ,0
Exp/Cntr=0.3,0.1

Type RM Length L Ch R = 1 ,3399    ,85,85,85
BEGIN DESCRIPTION:
Elm 01 21 3398.84
END DESCRIPTION:
XS GIS Cut Line= 3
      1515343.84      6806001.54      1515437.17      6805834.42
      1515465.38      6805545.81
#Sta/Elev= 30
  4814.2 2110.24  4868.8 2110.47  4906.5 2111.88  4912.2 2111.16  4933.9 2111.09
  4949.9 2106.06  4955.7 2101.29  4971.6 2095.83  4978.6 2092.72  4987.6 2092.69
  4991.3 2091.75  4991.6 2091.25  4995.1 2091.25  4995.3 2091.75  5000.7 2093.55
  5005.6 2093.55  5012.1 2098.34  5030.9 2107.25  5035.9 2105.78  5042.2 2109.57
  5052.3 2111.03  5102.5  2115.4  5112.5 2113.91  5132.6 2109.56  5137.6 2107.18
  5152.7 2109.13  5172.8 2113.13  5192.9  2120.2  5239.2 2124.75  5295.6 2128.61
#Mann= 3 ,-1 , 0
  4814.2     .07       0  4991.3     .07       0  4995.3     .07       0
Bank Sta=4991.3,4995.3
XS Rating Curve= 0 ,0
Exp/Cntr=0.3,0.1

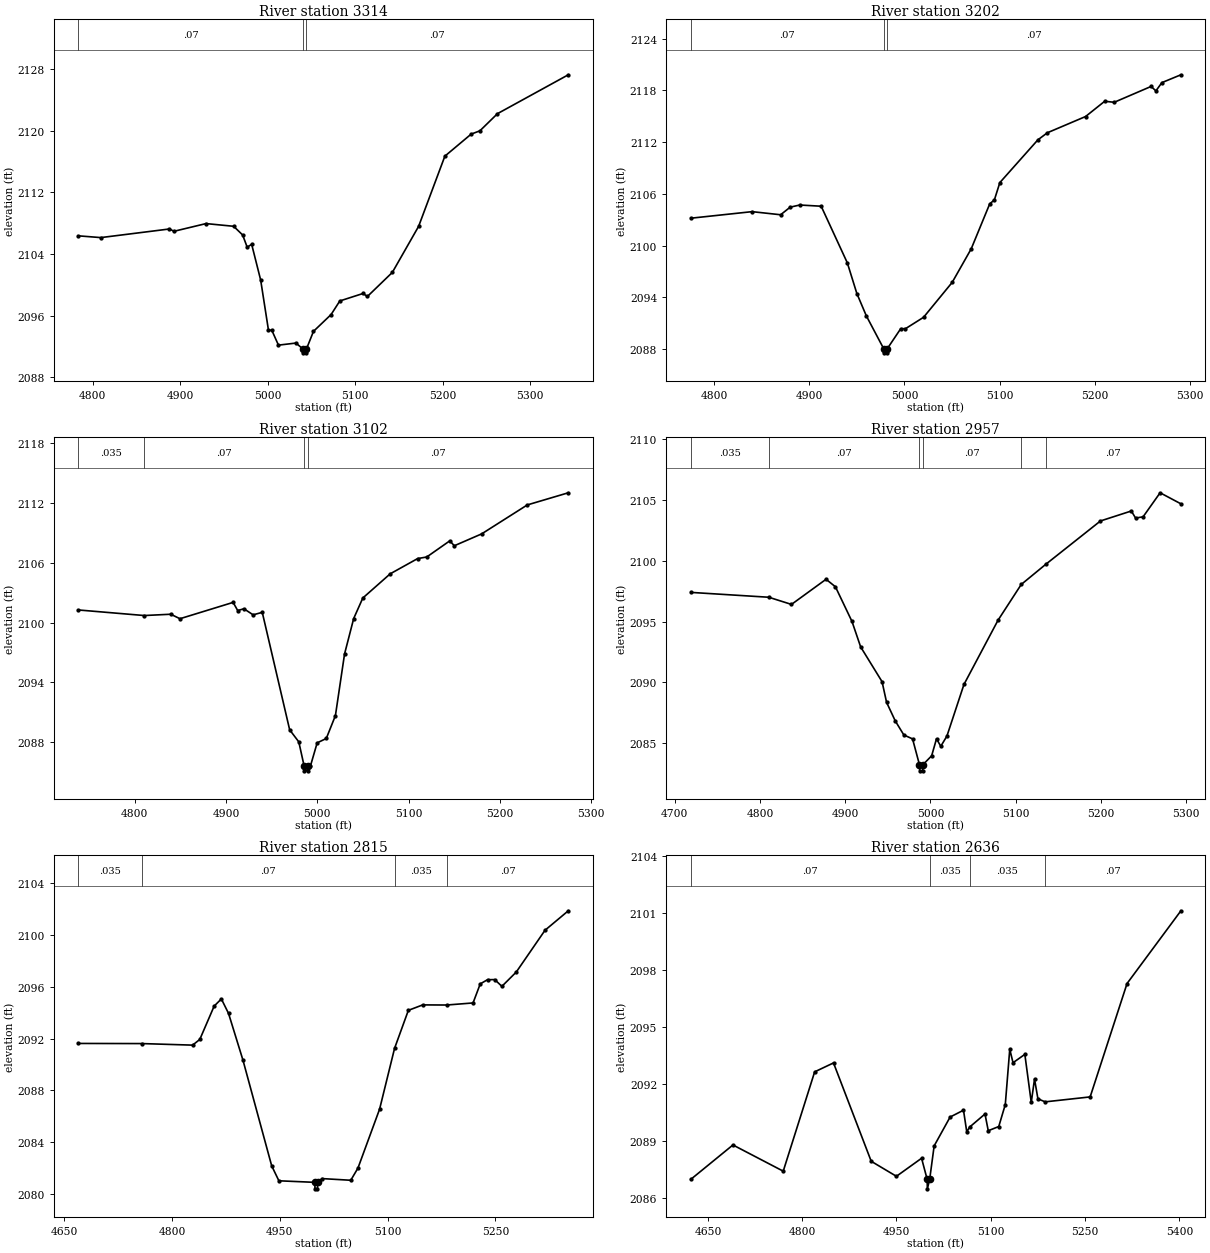
Type RM Length L Ch R = 1 ,3314    ,112,112,112
BEGIN DESCRIPTION:
Elm 01 21 3314.19
END DESCRIPTION:
XS GIS Cut Line= 3
      1515454.53       6806090.5      1515506.61      6805875.66
      1515517.46      6805537.09
#Sta/Elev= 30
  4783.6 2106.36  4809.4 2106.13  4887.8 2107.25    4893 2106.95  4929.6 2107.95
  4961.1  2107.6  4971.4 2106.47  4976.6 2104.88  4981.7 2105.26    4992 2100.61
  5000.9  2094.1  5004.7  2094.1  5012.3 2092.16  5032.3 2092.43  5040.3 2091.66
  5040.6 2091.16  5044.1 2091.16  5044.3 2091.66  5052.3 2093.95  5072.4 2096.13
  5082.4  2097.9  5108.9 2098.87  5113.9 2098.48  5142.4 2101.61  5172.4 2107.59
  5202.4 2116.71  5232.4 2119.57  5242.4    2120  5262.5 2122.23  5343.4 2127.28
#Mann= 3 ,-1 , 0
  4783.6     .07       0  5040.3     .07       0  5044.3     .07       0
Bank Sta=5040.3,5044.3
XS Rating Curve= 0 ,0
Exp/Cntr=0.3,0.1

Type RM Length L Ch R = 1 ,3202    ,100,100,100
BEGIN DESCRIPTION:
Elm 01 21 3201.84
END DESCRIPTION:
XS GIS Cut Line= 3
      1515593.42      6806062.31      1515604.27      6805840.93
      1515621.63      6805547.99
#Sta/Elev= 30
  4775.5 2103.18  4839.9 2103.94  4869.9 2103.58  4879.9 2104.46    4890 2104.71
  4912.5 2104.57    4940    2098    4950 2094.45    4960 2091.85  4978.1 2088.07
  4978.3 2087.57  4981.8 2087.57  4982.1 2088.07  4996.1 2090.37  5001.1 2090.37
  5020.1 2091.69  5050.2 2095.74  5070.2 2099.63  5089.6 2104.83  5094.6 2105.32
  5100.3 2107.31  5140.3 2112.27  5150.3 2113.09  5190.4 2114.97  5210.5 2116.74
  5220.5 2116.62  5259.3 2118.46  5264.3 2117.94  5270.6  2118.9  5290.6 2119.81
#Mann= 3 ,-1 , 0
  4775.5     .07       0  4978.1     .07       0  4982.1     .07       0
Bank Sta=4978.1,4982.1
XS Rating Curve= 0 ,0
Exp/Cntr=0.3,0.1

Type RM Length L Ch R = 1 ,3102    ,145,145,145
BEGIN DESCRIPTION:
Elm 01 21 3101.81
END DESCRIPTION:
XS GIS Cut Line= 3
      1515691.07      6806099.21       1515704.1      6805847.44
      1515714.95      6805563.15
#Sta/Elev= 30
  4738.2 2101.27  4810.5 2100.71  4839.5 2100.84  4849.6 2100.39  4907.8 2102.03
  4912.8 2101.21  4919.6 2101.39  4929.7 2100.78  4939.7 2101.03  4969.7 2089.23
  4979.7 2088.02  4985.5 2085.61  4985.8 2085.11  4989.3 2085.11  4989.5 2085.61
  4992.5 2085.61  4999.8 2087.92  5009.8 2088.36  5019.8 2090.66  5029.8 2096.85
  5039.8 2100.41  5049.8 2102.47  5079.8  2104.9  5109.8 2106.43  5119.8 2106.59
    5145 2108.21    5150 2107.72  5179.9 2108.91  5229.9 2111.82  5274.8 2113.04
#Mann= 4 ,-1 , 0
  4738.2    .035       0  4810.5     .07       0  4985.5     .07       0
  4989.5     .07       0
Bank Sta=4985.5,4989.5
XS Rating Curve= 0 ,0
Exp/Cntr=0.3,0.1

Type RM Length L Ch R = 1 ,2957    ,142,142,142
BEGIN DESCRIPTION:
Elm 01 21 2956.71
END DESCRIPTION:
XS GIS Cut Line= 3
      1515801.75      6806114.36      1515849.49      6805838.76
      1515862.51      6805543.65
#Sta/Elev= 30
  4718.8 2097.41  4810.3 2097.01  4836.9 2096.42  4877.5 2098.49  4888.5 2097.87
  4907.9 2095.02  4918.1 2092.92  4943.2 2090.06  4948.5 2088.36  4958.7 2086.83
  4968.8 2085.67    4979 2085.35  4987.1 2083.22  4987.4 2082.72  4990.9 2082.72
  4991.1 2083.22  5001.4 2083.96  5007.1 2085.36  5012.1 2084.74  5019.3 2085.58
  5039.3 2089.83  5079.3 2095.12  5106.5 2098.06  5135.1 2099.71  5199.5 2103.29
  5235.7 2104.11  5240.7 2103.53  5249.5 2103.63  5269.5 2105.61  5293.9  2104.7
#Mann= 6 ,-1 , 0
  4718.8    .035       0  4810.3     .07       0  4987.1     .07       0
  4991.1     .07       0  5106.5    .035       0  5135.1     .07       0
Bank Sta=4987.1,4991.1
XS Rating Curve= 0 ,0
Exp/Cntr=0.3,0.1

Type RM Length L Ch R = 1 ,2815    ,179,179,179
BEGIN DESCRIPTION:
Elm 01 21 2835.25
END DESCRIPTION:
XS GIS Cut Line= 3
      1515989.54      6806167.05      1515992.84      6805871.64
      1515978.56      6805485.63
#Sta/Elev= 30
  4669.7 2091.62  4758.4 2091.61  4828.8 2091.49  4838.8 2091.93  4858.8  2094.5
  4868.8 2095.05  4878.8 2093.93  4898.8 2090.34  4938.8 2082.19  4948.8 2081.04
  4998.8 2080.92    4999 2080.42  5002.5 2080.42  5002.8 2080.92  5008.8 2081.21
  5048.8 2081.08  5058.8 2082.02  5088.9 2086.56  5109.7 2091.24  5128.9 2094.17
  5148.9 2094.59  5182.1 2094.58  5218.9 2094.74  5228.9 2096.21    5239 2096.53
    5249 2096.54    5259 2096.02    5279 2097.12    5319 2100.34  5351.4 2101.84
#Mann= 4 ,-1 , 0
  4669.7    .035       0  4758.4     .07       0  5109.7    .035       0
  5182.1     .07       0
Bank Sta=4998.8,5002.8
XS Rating Curve= 0 ,0
Exp/Cntr=0.3,0.1

Type RM Length L Ch R = 1 ,2636    ,60,60,60
BEGIN DESCRIPTION:
Elm 01 21 2697.97
END DESCRIPTION:
XS GIS Cut Line= 3
      1516143.82      6806164.92      1516155.88      6805752.28
      1516057.46      6805398.85
#Sta/Elev= 30
  4622.8 2086.98  4689.8 2088.79  4769.8 2087.41  4819.8 2092.64  4849.8 2093.11
  4909.8 2087.93  4949.9 2087.14  4989.9 2088.09  4998.8 2086.98  4999.1 2086.48
  5002.8 2086.98  5009.9 2088.74  5035.3 2090.26  5056.6 2090.62  5061.8 2089.48
  5066.3 2089.73  5090.8 2090.42    5096 2089.54  5112.7 2089.76  5123.1 2090.92
  5130.2 2093.83  5135.4 2093.12  5154.2 2093.56  5164.4 2091.03  5169.6 2092.26
    5175 2091.22  5186.5 2091.06  5258.1 2091.32  5316.8 2097.29  5402.5 2101.12
#Mann= 4 ,-1 , 0
  4622.8     .07       0  5002.8    .035       0  5066.3    .035       0
  5186.5     .07       0
Bank Sta=4998.8,5002.8
XS Rating Curve= 0 ,0
Exp/Cntr=0.3,0.1

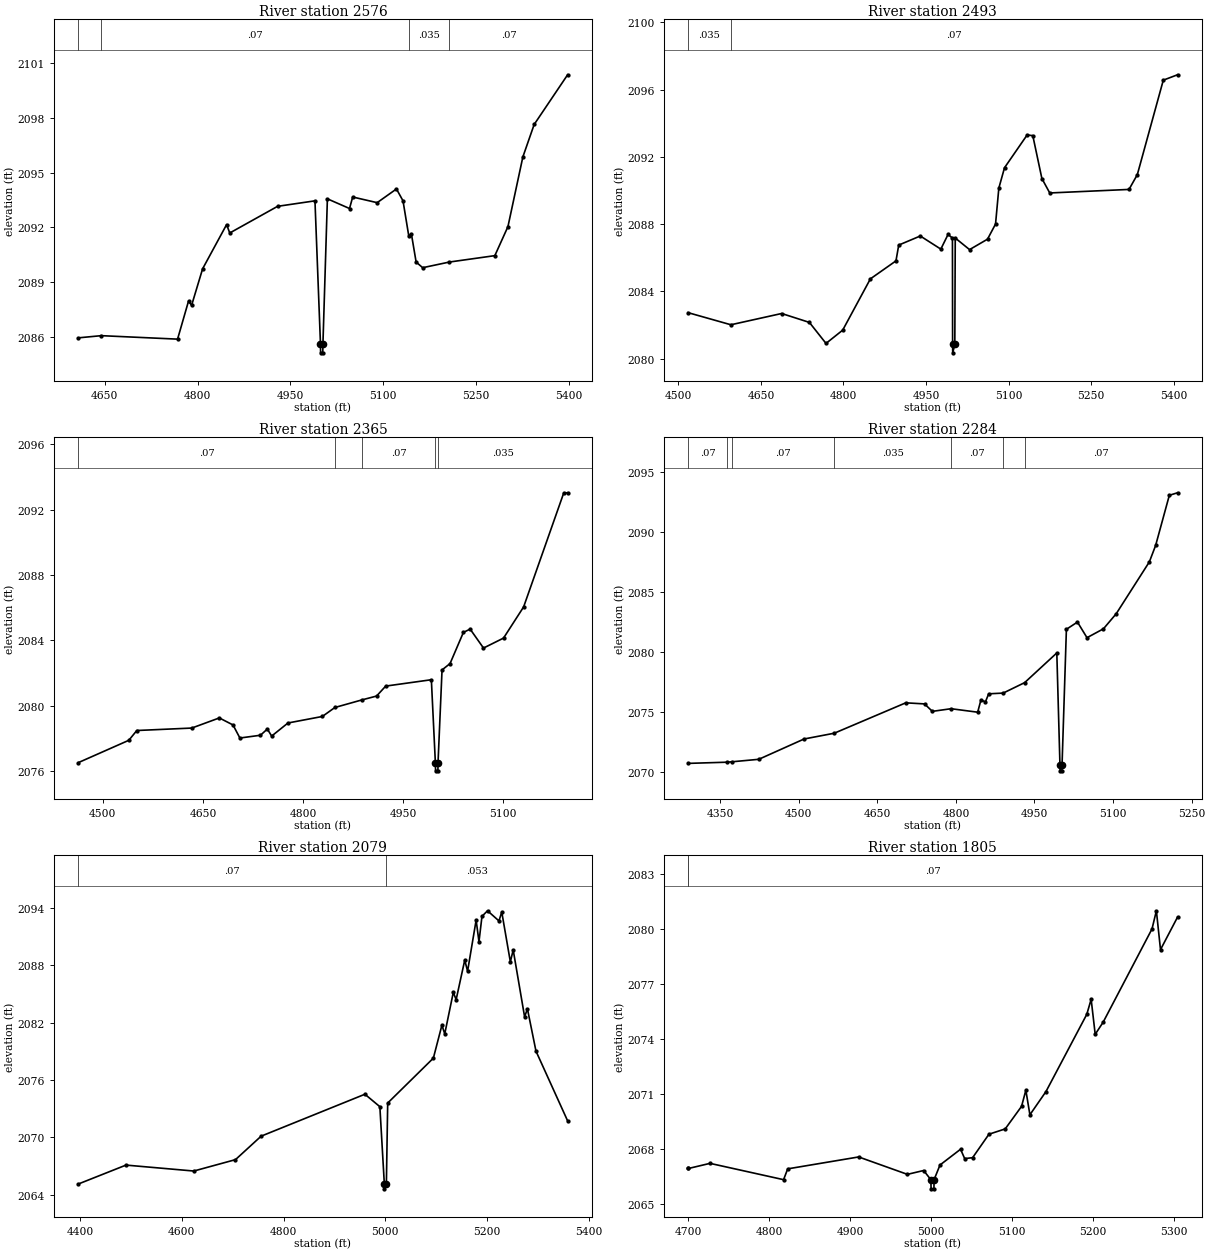
Type RM Length L Ch R = 1 ,2576    ,83,83,83
BEGIN DESCRIPTION:
Elm 01 21 2561.4
END DESCRIPTION:
XS GIS Cut Line= 4
       1516193.2      6806178.32      1516226.86      6805894.09
      1516203.93      6805686.95      1516105.08      6805407.01
#Sta/Elev= 30
    4607 2085.95  4644.4 2086.07  4767.7 2085.88  4785.4 2087.96  4790.4 2087.73
  4808.2 2089.73    4847 2092.15  4852.1 2091.69  4929.5 2093.15  4989.9 2093.45
  4998.8 2085.63    4999 2085.13  5002.5 2085.13  5002.8 2085.63    5010 2093.56
  5045.8 2093.03  5050.9 2093.66  5090.5 2093.35  5121.7  2094.1  5132.3 2093.45
  5141.7 2091.51  5145.8 2091.65  5153.5  2090.1  5164.1 2089.79  5207.3  2090.1
  5280.8 2090.45    5302 2092.04  5326.1 2095.85  5344.4 2097.63  5398.5 2100.35
#Mann= 4 ,-1 , 0
    4607    .035       0  4644.4     .07       0  5141.7    .035       0
  5207.3     .07       0
Bank Sta=4998.8,5002.8
XS Rating Curve= 0 ,0
Exp/Cntr=0.3,0.1

Type RM Length L Ch R = 1 ,2493    ,128,128,128
BEGIN DESCRIPTION:
Elm 01 21 2457.39
END DESCRIPTION:
XS GIS Cut Line= 4
      1516129.34      6806235.95      1516301.34       6805819.9
      1516297.33      6805787.01      1516202.94      6805392.28
#Sta/Elev= 30
  4517.7 2082.73  4595.5 2082.01  4687.7 2082.68  4738.1 2082.15  4768.3  2080.9
  4798.6 2081.69  4848.9 2084.74  4895.4 2085.81  4900.4 2086.75  4939.6 2087.29
  4976.9 2086.51    4990 2087.38    4998 2087.17  4998.3 2080.84  4998.5 2080.34
  5002.3 2080.84  5003.1 2087.17  5029.1 2086.48  5061.7  2087.1  5076.3    2088
  5082.3 2090.14  5092.6 2091.35  5133.7  2093.3    5144 2093.26  5160.5 2090.71
  5174.8 2089.85  5318.8 2090.06  5333.9 2090.94  5381.1 2096.56  5406.9 2096.88
#Mann= 2 ,-1 , 0
  4517.7    .035       0  4595.5     .07       0
Bank Sta=4998.3,5002.3
XS Rating Curve= 0 ,0
Exp/Cntr=0.3,0.1

Type RM Length L Ch R = 1 ,2365    ,81,81,81
BEGIN DESCRIPTION:
Elm 01 21 2368.58
END DESCRIPTION:
XS GIS Cut Line= 3
      1516079.73      6806167.36      1516429.59      6805857.64
      1516415.94      6805592.15
#Sta/Elev= 30
  4463.2  2076.5    4539 2077.87    4551 2078.47  4633.3 2078.62  4674.6 2079.24
  4695.1 2078.81  4705.4 2078.01  4736.2 2078.18  4746.5 2078.56    4753 2078.13
  4777.4 2078.93  4828.9 2079.33  4847.7 2079.88  4887.8 2080.34  4910.1 2080.58
  4923.8 2081.19  4992.2 2081.58  4998.2  2076.5  4998.5    2076    5002    2076
  5002.2  2076.5  5008.2 2082.18  5020.2 2082.57  5040.2 2084.48  5050.3 2084.68
  5070.3 2083.52  5100.3 2084.13  5130.4 2086.04  5190.4 2093.01  5196.3 2093.03
#Mann= 5 ,-1 , 0
  4463.2     .07       0  4847.7    .035       0  4887.8     .07       0
  4998.2     .07       0  5002.2    .035       0
Bank Sta=4998.2,5002.2
XS Rating Curve= 0 ,0
Exp/Cntr=0.3,0.1

Type RM Length L Ch R = 1 ,2284    ,205,205,205
BEGIN DESCRIPTION:
Elm 01 21 2233.75
END DESCRIPTION:
XS GIS Cut Line= 3
      1516627.54      6806488.67      1516514.28       6805810.2
      1516435.38      6805577.15
#Sta/Elev= 30
    4289 2070.75  4363.6 2070.85  4371.9 2070.88  4423.9 2071.09  4510.3 2072.78
  4567.9 2073.26  4704.4 2075.79  4740.2  2075.7  4755.1 2075.08  4790.9  2075.3
  4841.6 2075.01  4847.7 2076.01  4856.5 2075.88  4862.6 2076.54  4890.2  2076.6
  4931.2 2077.47  4992.6 2079.94  4998.6 2070.63  4998.9 2070.13  5002.4 2070.13
  5002.6 2070.63  5010.9 2081.91    5032 2082.51  5050.2 2081.21  5081.6 2081.95
  5105.9  2083.2  5169.2 2087.52  5181.2 2088.89  5207.3 2093.06  5222.9 2093.27
#Mann= 7 ,-1 , 0
    4289     .07       0  4363.6    .035       0  4371.9     .07       0
  4567.9    .035       0  4790.9     .07       0  4890.2    .035       0
  4931.2     .07       0
Bank Sta=4998.6,5002.6
XS Rating Curve= 0 ,0
Exp/Cntr=0.3,0.1

Type RM Length L Ch R = 1 ,2079    ,274,274,274
BEGIN DESCRIPTION:
Elm 01 21 2114.32
END DESCRIPTION:
XS GIS Cut Line= 4
      1516738.04      6806387.68      1516731.17      6805828.15
      1516698.98      6805763.09      1516660.92      6805435.05
#Sta/Elev= 30
  4396.2 2065.13  4490.2 2067.11  4623.5 2066.49  4705.5 2067.68  4755.9 2070.13
    4960 2074.51  4989.4 2073.21  4998.2 2065.13  4998.4 2064.63  5002.2 2065.13
  5004.8 2073.59  5094.6 2078.28  5111.4 2081.72    5117 2080.82  5133.8 2085.15
  5139.4 2084.39  5156.3 2088.52  5161.9 2087.36  5178.7 2092.69  5184.3 2090.44
  5190.2 2093.09  5201.1 2093.67  5223.6 2092.61  5229.1 2093.54    5246 2088.34
  5251.6 2089.58    5274  2082.6  5279.6 2083.42  5296.4 2079.01  5358.6 2071.73
#Mann= 2 ,-1 , 0
  4396.2     .07       0  5002.2    .053       0
Bank Sta=4998.2,5002.2
XS Rating Curve= 0 ,0
Exp/Cntr=0.3,0.1

Type RM Length L Ch R = 1 ,1805    ,61,61,61
BEGIN DESCRIPTION:
Elm 01 21 1851.854
END DESCRIPTION:
XS GIS Cut Line= 4
      1516838.81      6806038.13      1516973.79      6805882.44
      1516989.45      6805756.98      1516817.64      6805545.71
#Sta/Elev= 30
  4699.6 2066.92    4700 2066.92  4726.7  2067.2  4817.6 2066.31  4822.7  2066.9
  4910.4 2067.55  4970.6  2066.6  4990.7 2066.81  4999.6 2066.31  4999.9 2065.81
  5003.4 2065.81  5003.6 2066.31  5010.9 2067.11  5036.3 2067.97  5041.4 2067.46
  5051.2 2067.51  5071.4 2068.79  5091.5 2069.08  5111.7 2070.31    5117 2071.19
    5122 2069.85  5141.9 2071.12  5192.3 2075.33  5197.7 2076.15  5202.7 2074.24
  5212.5  2074.9  5272.9 2079.99  5278.3 2080.98  5283.4 2078.86  5304.4 2080.63
#Mann= 2 ,-1 , 0
  4699.6    .035       0    4700     .07       0
Bank Sta=4999.6,5003.6
XS Rating Curve= 0 ,0
Exp/Cntr=0.3,0.1

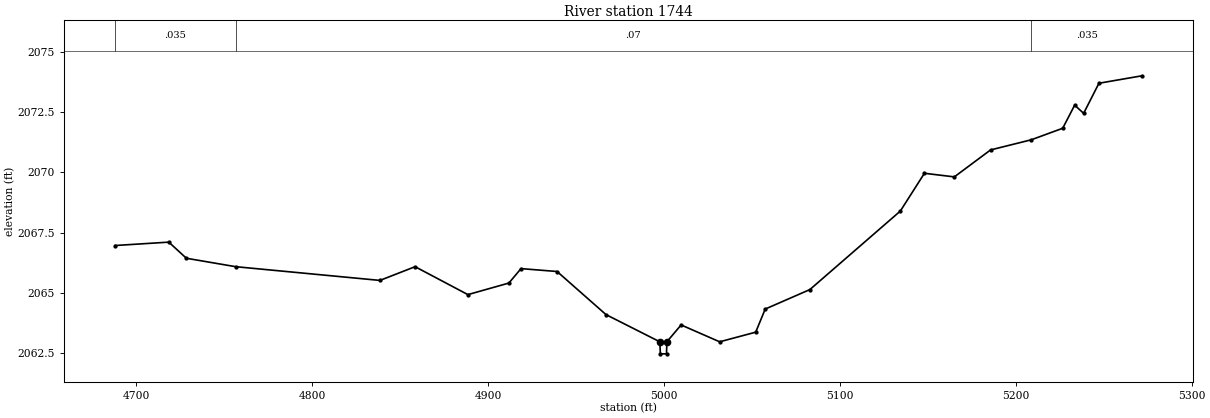
Type RM Length L Ch R = 1 ,1744    ,175,175,175
BEGIN DESCRIPTION:
Elm 01 21 1719.487
END DESCRIPTION:
XS GIS Cut Line= 3
      1517073.19      6806093.62       1517027.1      6805874.71
      1517108.27      6805524.09
#Sta/Elev= 30
  4688.2 2066.96  4718.6  2067.1  4728.6 2066.43  4756.6 2066.08  4838.6 2065.51
  4858.6 2066.08  4888.6 2064.92  4911.9  2065.4  4918.8    2066  4939.3 2065.88
  4967.1 2064.09  4997.7 2062.96    4998 2062.46  5001.5 2062.46  5001.7 2062.96
  5009.8 2063.66  5031.7 2062.96  5052.2 2063.36  5057.6 2064.32    5083 2065.13
  5134.4 2068.39  5148.1 2069.96  5165.1 2069.81  5185.7 2070.93  5208.8 2071.35
  5226.7 2071.83  5233.5 2072.79  5238.6 2072.45  5247.3  2073.7  5271.8 2074.01
#Mann= 3 ,-1 , 0
  4688.2    .035       0  4756.6     .07       0  5208.8    .035       0
Bank Sta=4997.7,5001.7
XS Rating Curve= 0 ,0
Exp/Cntr=0.3,0.1