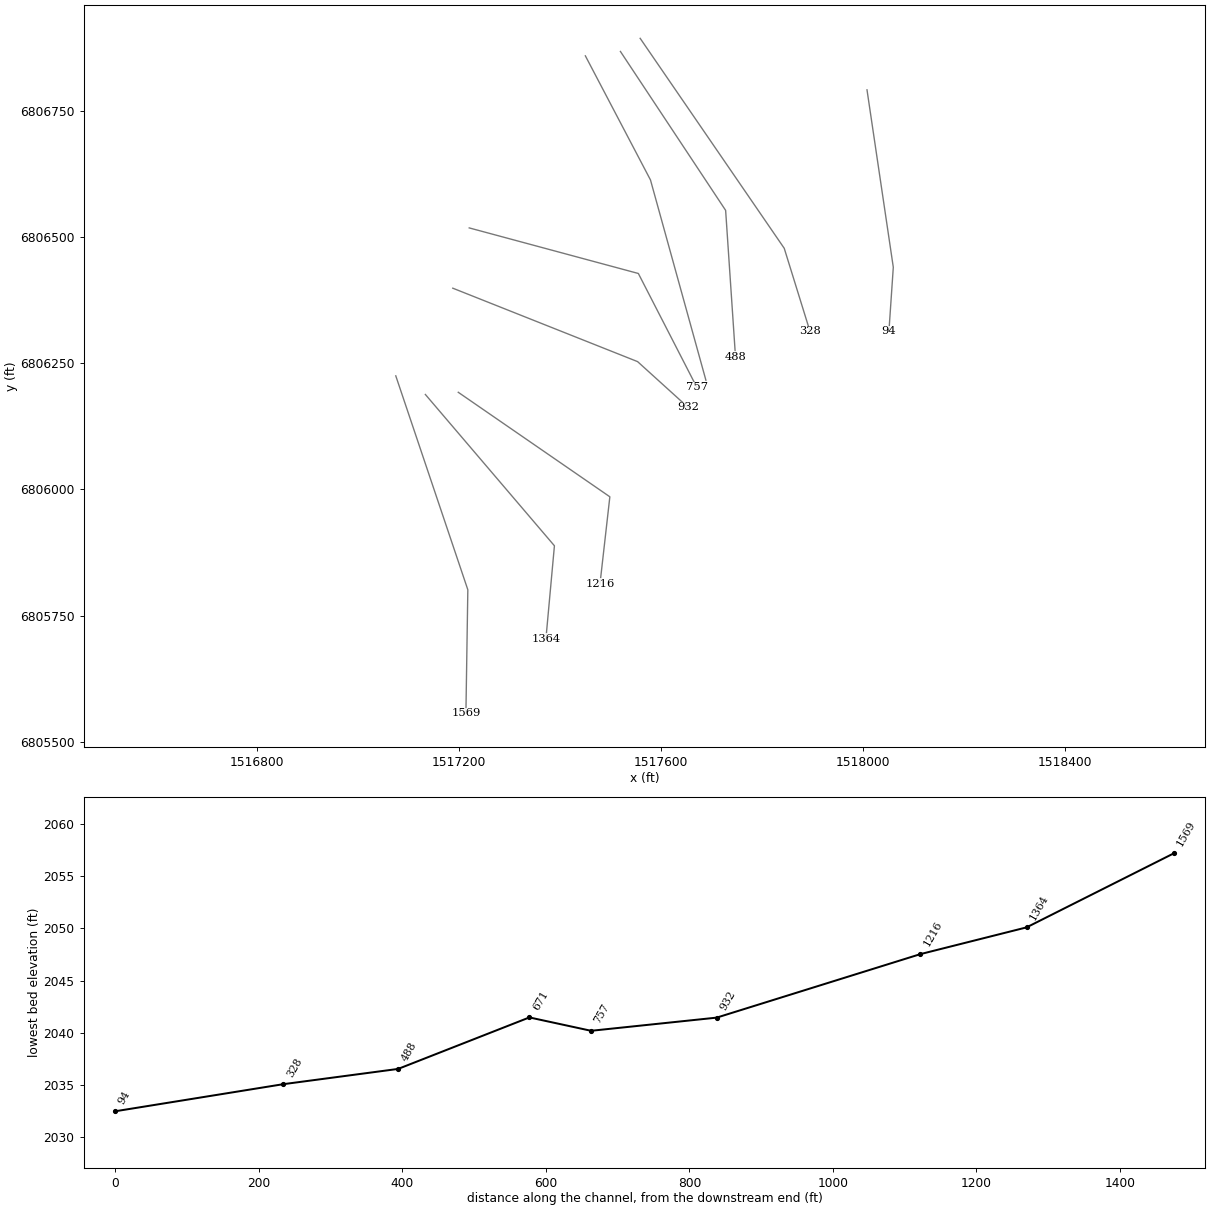
HEC-RAS study Elm 01 21.prj: Elm 01 21 Base Level Engineering

--- Elm 01 21.g01 (geometry) --- (continued)

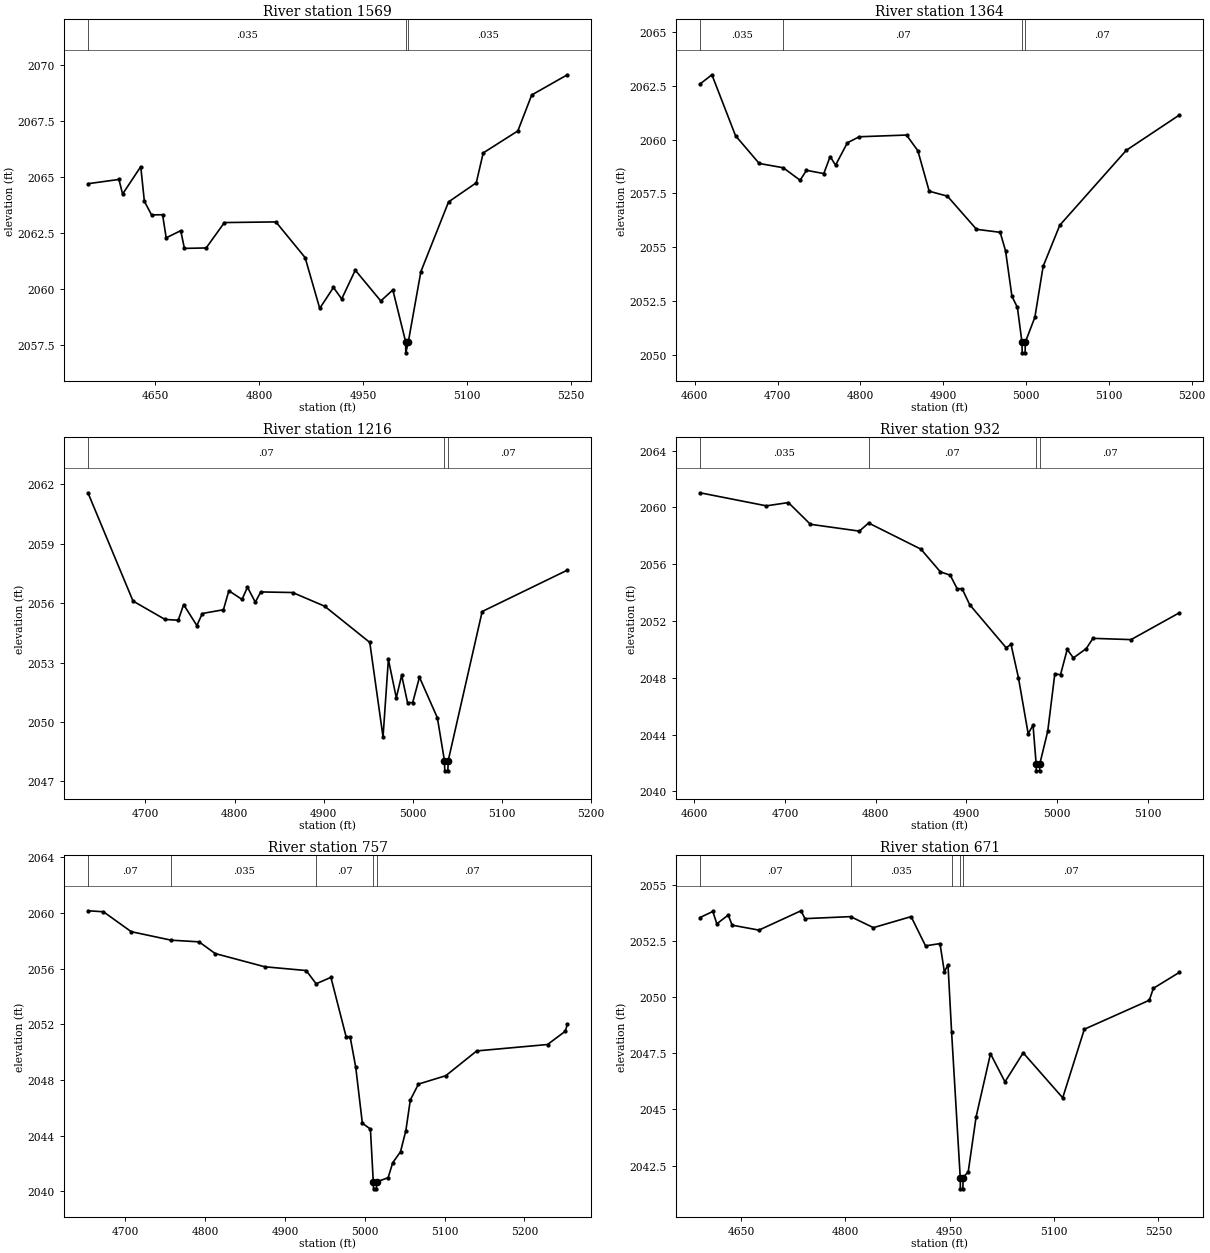
Type RM Length L Ch R = 1 ,1569    ,205,205,205
BEGIN DESCRIPTION:
Elm 01 21 1569.131
END DESCRIPTION:
XS GIS Cut Line= 3
      1517075.63      6806225.02      1517218.31       6805801.4
      1517214.51      6805556.63
#Sta/Elev= 30
    4553  2064.7  4597.7 2064.89    4603 2064.24  4629.2 2065.46  4634.4 2063.92
  4644.8 2063.31  4660.7 2063.32  4665.9 2062.29  4686.9 2062.61  4692.2 2061.82
  4723.6 2061.84  4749.9 2062.97  4824.2    2063  4866.4 2061.41  4887.5 2059.15
  4907.3 2060.08  4919.2 2059.57  4938.8 2060.85  4975.6 2059.48    4993 2059.97
  5011.4 2057.67  5011.7 2057.17  5015.4 2057.67  5033.4 2060.78  5073.4 2063.89
  5113.4 2064.74  5123.4 2066.07  5173.4 2067.05  5193.4 2068.65  5244.8 2069.55
#Mann= 3 ,-1 , 0
    4553    .035       0  5011.4    .035       0  5015.4    .035       0
Bank Sta=5011.4,5015.4
XS Rating Curve= 0 ,0
Exp/Cntr=0.3,0.1

Type RM Length L Ch R = 1 ,1364    ,148,148,148
BEGIN DESCRIPTION:
Elm 01 21 1364.228
END DESCRIPTION:
XS GIS Cut Line= 3
      1517134.23      6806188.14      1517389.79      6805888.52
      1517372.93      6805704.19
#Sta/Elev= 30
  4606.2 2062.58  4620.6 2063.01  4649.1 2060.18  4677.7 2058.89  4706.7 2058.69
  4727.1 2058.11  4734.8 2058.57  4755.7 2058.42  4763.4 2059.21  4769.9 2058.81
  4784.2 2059.85  4798.5 2060.13  4855.6 2060.21  4869.3 2059.48    4883  2057.6
    4905 2057.37  4940.1 2055.83  4968.7 2055.69  4975.2 2054.83  4982.9 2052.72
  4989.5  2052.2    4995 2050.59  4995.3 2050.09  4998.8 2050.09  4999.1 2050.59
  5010.6 2051.74  5020.6 2054.11  5040.7 2056.02    5121  2059.5  5185.1 2061.14
#Mann= 4 ,-1 , 0
  4606.2    .035       0  4706.7     .07       0    4995     .07       0
  4999.1     .07       0
Bank Sta=4995,4999.1
XS Rating Curve= 0 ,0
Exp/Cntr=0.3,0.1

Type RM Length L Ch R = 1 ,1216    ,284,284,284
BEGIN DESCRIPTION:
Elm 01 21 1215.588
END DESCRIPTION:
XS GIS Cut Line= 3
      1517199.36      6806192.47      1517499.55      6805985.53
        1517480.      6805813.04
#Sta/Elev= 30
  4635.4 2061.58    4686 2056.11  4721.9 2055.18  4736.8 2055.14  4742.8 2055.93
  4757.7 2054.87  4763.8 2055.48  4787.5 2055.67  4793.6 2056.63  4808.4 2056.19
  4814.5 2056.81  4823.3 2056.05  4829.4 2056.57  4865.2 2056.54  4901.1 2055.85
  4951.8 2054.02  4966.7 2049.24  4972.7 2053.16  4981.6 2051.22  4987.6 2052.36
  4994.2 2050.98    5000 2050.98  5007.6 2052.26  5027.7 2050.21  5035.7 2048.03
    5036 2047.53  5039.5 2047.53  5039.8 2048.03    5078 2055.58  5173.6 2057.67
#Mann= 3 ,-1 , 0
  4635.4     .07       0  5035.7     .07       0  5039.8     .07       0
Bank Sta=5035.7,5039.8
XS Rating Curve= 0 ,0
Exp/Cntr=0.3,0.1

Type RM Length L Ch R = 1 ,932     ,175,175,175
BEGIN DESCRIPTION:
Elm 01 21 931.67
END DESCRIPTION:
XS GIS Cut Line= 3
      1517188.51      6806398.64      1517554.48      6806253.22
      1517654.53      6806162.59
#Sta/Elev= 30
  4606.2 2061.03  4679.4 2060.11  4703.7 2060.34    4728 2058.81    4782 2058.33
  4792.2  2058.9  4849.9 2057.06  4871.4 2055.46  4882.2 2055.23  4889.9 2054.27
  4895.3 2054.28  4903.7 2053.15  4943.9 2050.12  4949.3 2050.35  4957.5    2048
  4968.2 2044.07  4973.6 2044.66    4977 2041.95  4977.2 2041.45  4980.8 2041.45
  4981.1 2041.95  4989.8 2044.24  4997.6 2048.27  5003.9 2048.22  5011.3    2050
  5018.1  2049.4  5032.3 2050.06  5039.7 2050.78  5081.7 2050.69    5135 2052.58
#Mann= 4 ,-1 , 0
  4606.2    .035       0  4792.2     .07       0    4977     .07       0
  4981.1     .07       0
Bank Sta=4977,4981.1
XS Rating Curve= 0 ,0
Exp/Cntr=0.3,0.1

Type RM Length L Ch R = 1 ,757     ,86,86,86
BEGIN DESCRIPTION:
Elm 01 21 757.116
END DESCRIPTION:
XS GIS Cut Line= 3
      1517221.05      6806518.01        1517556.      6806427.76
      1517671.94       6806202.1
#Sta/Elev= 30
  4653.1 2060.15  4672.5 2060.08  4707.3 2058.65  4757.3 2058.04  4792.3 2057.92
  4812.5 2057.08  4874.7 2056.13  4926.5 2055.86    4939 2054.91  4957.5 2055.37
  4976.5 2051.12  4981.6  2051.1  4988.6 2048.92  4996.9  2044.9    5007 2044.48
  5010.6 2040.69  5010.9 2040.19  5014.5 2040.19  5014.7 2040.69  5029.2 2040.99
  5034.9 2042.06  5044.7 2042.85  5051.4 2044.37    5057 2046.57  5067.2 2047.71
  5101.4 2048.31  5140.2 2050.09  5228.9 2050.55  5251.1  2051.5  5253.7 2051.99
#Mann= 5 ,-1 , 0
  4653.1     .07       0  4757.3    .035       0    4939     .07       0
  5010.6     .07       0  5014.7     .07       0
Bank Sta=5010.6,5014.7
XS Rating Curve= 0 ,0
Exp/Cntr=0.3,0.1

Type RM Length L Ch R = 1 ,671     ,183,183,183
BEGIN DESCRIPTION:
Elm 01 21 670.573
END DESCRIPTION:
XS GIS Cut Line= 3
      1517451.05      6806858.75        1517580.        6806613.
      1517689.78      6806216.34
#Sta/Elev= 30
  4591.1 2053.54  4609.6 2053.81  4615.3 2053.26  4631.7 2053.65  4637.3  2053.2
  4675.8 2052.98  4736.3 2053.84    4742 2053.49  4807.6 2053.58  4840.4 2053.09
  4894.6 2053.58  4915.3 2052.28  4936.1 2052.38  4942.4 2051.12  4947.6 2051.44
  4952.8 2048.44  4965.2 2041.97  4965.4 2041.47    4969 2041.47  4969.3 2041.97
  4976.7 2042.23    4988 2044.67  5008.7 2047.48  5029.5 2046.23  5055.7 2047.52
  5112.5 2045.52  5143.6 2048.57    5237 2049.86  5242.8 2050.39  5280.2  2051.1
#Mann= 5 ,-1 , 0
  4591.1     .07       0  4807.6    .035       0  4952.8     .07       0
  4965.2     .07       0  4969.3     .07       0
Bank Sta=4965.2,4969.3
XS Rating Curve= 0 ,0
Exp/Cntr=0.3,0.1

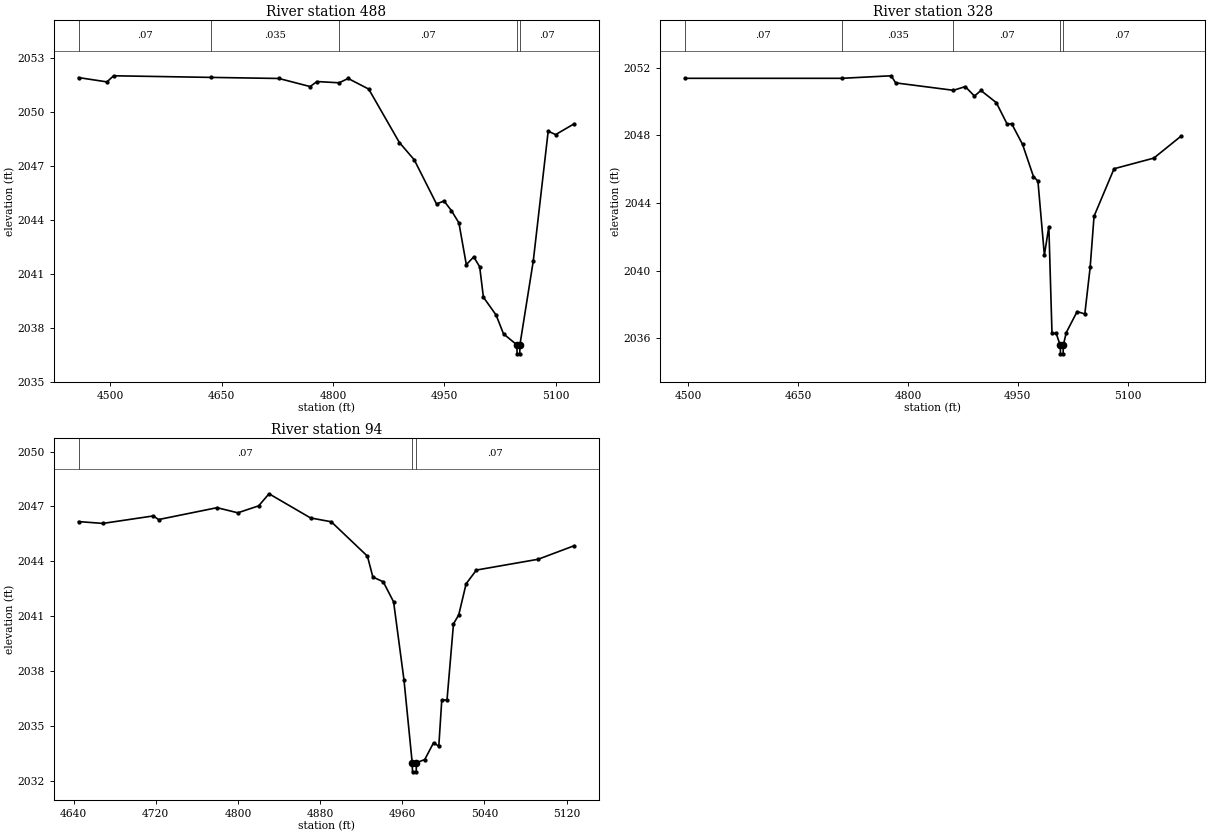
Type RM Length L Ch R = 1 ,488     ,160,160,160
BEGIN DESCRIPTION:
Elm 01 21 488.023
END DESCRIPTION:
XS GIS Cut Line= 3
      1517520.48      6806867.45      1517728.84      6806552.74
      1517748.36      6806263.03
#Sta/Elev= 30
    4457  2051.9  4495.3 2051.66  4504.3    2052  4635.5 2051.91    4727 2051.85
  4769.1  2051.4  4778.2 2051.68  4808.1 2051.61  4820.3 2051.85    4848 2051.26
  4889.3 2048.29  4909.3 2047.33  4939.4 2044.87  4949.4 2045.04  4959.5  2044.5
  4969.5 2043.82  4979.5  2041.5  4989.5 2041.93  4997.5 2041.38  5002.5 2039.69
  5019.6  2038.7  5029.6 2037.65  5047.6 2037.04  5047.9 2036.54  5051.5 2036.54
  5051.7 2037.04  5069.7  2041.7  5089.8 2048.92  5099.8 2048.73  5124.8 2049.33
#Mann= 5 ,-1 , 0
    4457     .07       0  4635.5    .035       0  4808.1     .07       0
  5047.6     .07       0  5051.7     .07       0
Bank Sta=5047.6,5051.7
XS Rating Curve= 0 ,0
Exp/Cntr=0.3,0.1

Type RM Length L Ch R = 1 ,328     ,234,234,234
BEGIN DESCRIPTION:
Elm 01 21 328.208
END DESCRIPTION:
XS GIS Cut Line= 3
      1517559.58      6806893.42       1517844.9       6806477.6
      1517895.93      6806313.03
#Sta/Elev= 30
  4495.7 2051.38  4709.6 2051.38  4777.2 2051.53  4783.3 2051.11  4862.2 2050.67
  4878.2 2050.89  4890.9 2050.33  4899.7 2050.66  4920.7 2049.94  4935.6 2048.66
  4941.6  2048.7  4956.5 2047.47  4971.4 2045.57  4977.5  2045.3  4986.3 2040.92
  4992.4 2042.61  4996.7 2036.29  5002.4 2036.29    5008 2035.58  5008.3 2035.08
  5011.9 2035.08  5012.1 2035.58  5016.2 2036.34    5031 2037.58  5041.5 2037.44
  5048.8  2040.2  5054.1 2043.22  5081.4 2046.03  5135.7 2046.66  5172.3 2047.94
#Mann= 5 ,-1 , 0
  4495.7     .07       0  4709.6    .035       0  4862.2     .07       0
    5008     .07       0  5012.1     .07       0
Bank Sta=5008,5012.1
XS Rating Curve= 0 ,0
Exp/Cntr=0.3,0.1

Type RM Length L Ch R = 1 ,94      ,0,0,0
BEGIN DESCRIPTION:
Elm 01 21 94.288
END DESCRIPTION:
XS GIS Cut Line= 3
      1518008.78      6806791.46      1518060.87       6806440.1
      1518052.19        6806313.
#Sta/Elev= 30
  4644.8 2046.17  4668.5 2046.07  4717.7 2046.48  4722.7 2046.28  4779.7 2046.93
  4799.9 2046.65  4820.2 2047.03  4830.3 2047.69  4870.7 2046.37  4890.9 2046.16
  4926.1 2044.28  4931.4 2043.14  4941.5 2042.88  4951.6 2041.78  4961.7 2037.51
  4969.7 2032.99    4970 2032.49  4973.6 2032.49  4973.8 2032.99  4981.9 2033.16
  4990.5 2034.08  4995.6 2033.89  4998.5 2036.42  5003.6 2036.42  5009.9 2040.58
    5015 2041.07  5022.2 2042.77  5032.2 2043.52  5092.3 2044.11  5127.4 2044.85
#Mann= 3 ,-1 , 0
  4644.8     .07       0  4969.7     .07       0  4973.8     .07       0
Bank Sta=4969.7,4973.8
XS Rating Curve= 0 ,0
Exp/Cntr=0.3,0.1

Chan Stop Cuts=-1
Use User Specified Reach Order=0
Composite Channel Slope=5