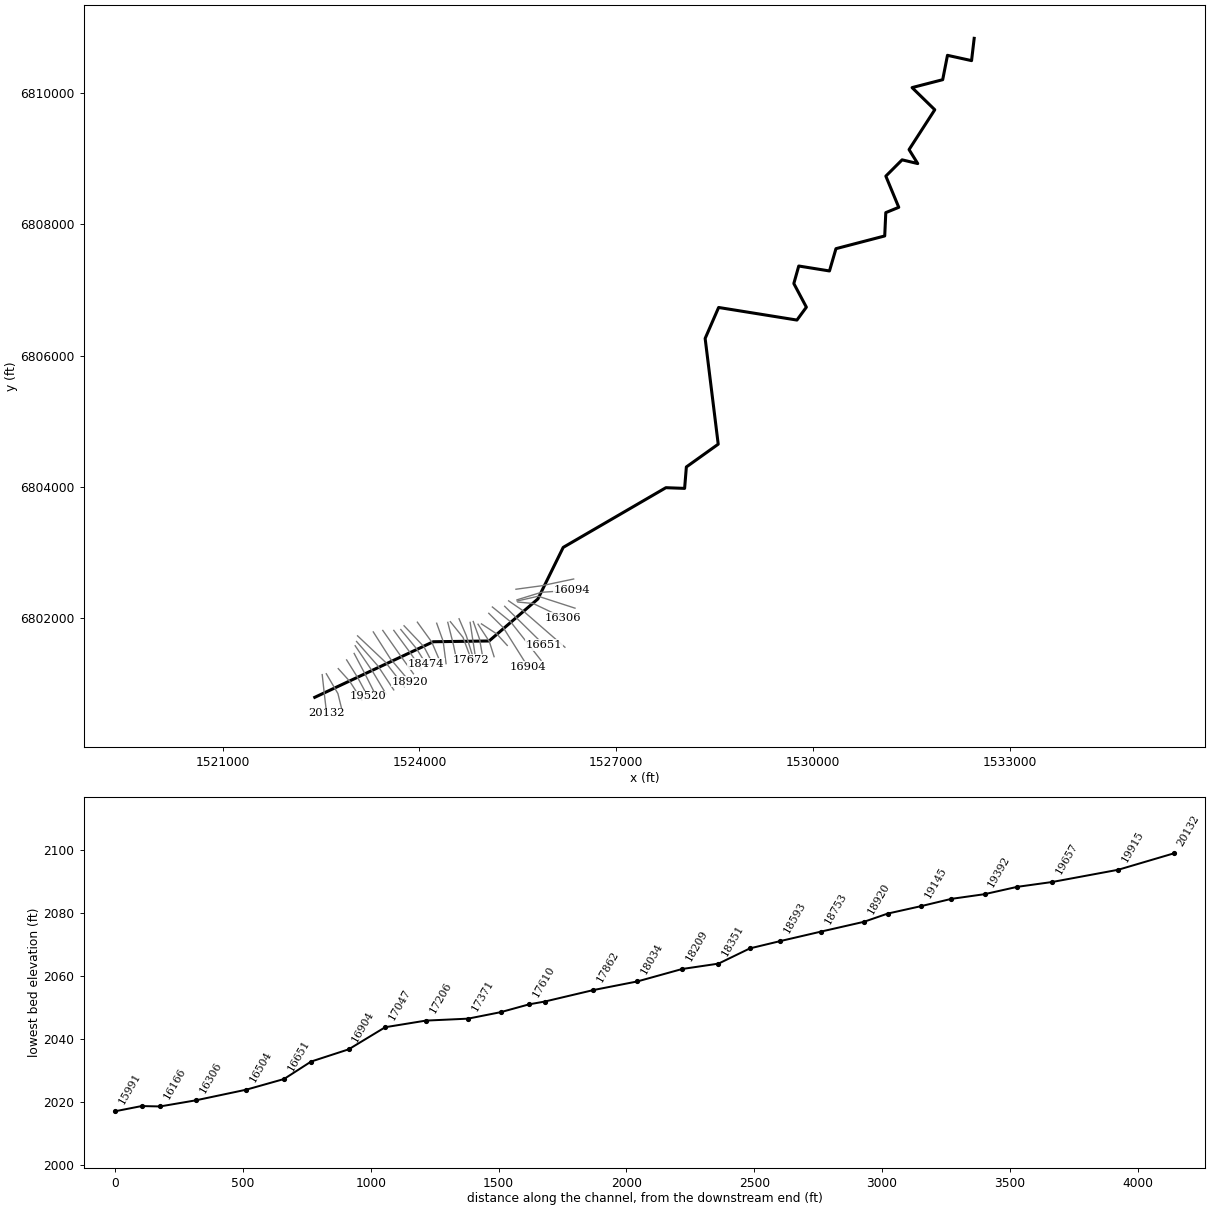
--- Elm 01 22.prj (project) ---

Proj Title=Elm 01 22 Base Level Engineering
Current Plan=p01
Default Exp/Contr=0.3,0.1
English Units
Geom File=g01
Flow File=f01
Plan File=p01
Y Axis Title=Elevation
X Axis Title(PF)=Main Channel Distance
X Axis Title(XS)=Station
BEGIN DESCRIPTION:
Elm 01 22
END DESCRIPTION:
DSS Export Rating Curves= 0
DSS Export Rating Curve Sorted= 0
DSS Export Volume Flow Curves= 0
DXF OffsetX= 0
DXF OffsetY= 0
DXF ScaleX= 1
DXF ScaleY= 10

--- Elm 01 22.p01 (plan) ---

Plan Title=Multiple Run
Program Version=4.10
Short Identifier=Multiple
Geom File=g01
Flow File=f01
Subcritical Flow
K Sum by GR= 0
Std Step Tol= 0.01
Critical Tol= 0.01
Num of Std Step Trials= 20
Max Error Tol= 0.3
Flow Tol Ratio= 0.001
Split Flow NTrial= 30
Split Flow Tol= 0.02
Split Flow Ratio= 0.02
Log Output Level= 0
Friction Slope Method= 1
Unsteady Friction Slope Method= 2
Unsteady Bridges Friction Slope Method= 1
Parabolic Critical Depth
Global Vel Dist= 1 , 1 , 1
Global Log Level= 0
CheckData=True
Encroach Param=-1 ,0,0, 0
BEGIN DESCRIPTION:
Multiple Run
END DESCRIPTION:
Computation Interval=1HOUR
Output Interval=1HOUR
Run HTab= 0
Run UNet= 0
Run PostProcess= 0
Run WQNet= 0
UNET Theta= 1
UNET Theta Warmup= 1
UNET ZTol= 0.02
UNET ZSATol= 0.05
UNET MxIter= 20
UNET MaxInSteps= 0
UNET DtIC= 0
UNET DtMin= 0
UNET MaxCRTS= 20
UNET WFStab= 2
UNET SFStab= 1
UNET WFX= 1
UNET SFX= 1
UNET DSS MLevel= 4
UNET DZMax Abort= 100
UNET Convert EG Bridges= 0
UNET Use Existing IB Tables=-1
UNET Froude Reduction=False
UNET Froude Limit= 1
UNET Froude Power= 10
UNET Time Slicing=0,0, 5
UNET Junction Losses=0
Instantaneous Interval=1HOUR
Write IC File= 0
Write IC File at Sim End=0
Echo Input=False
Echo Parameters=False
Echo Output=False
Write Detailed= 0
WQ AD Non Conservative
WQ ULTIMATE=-1
WQ Max Comp Step=1HOUR
WQ Output Interval=15MIN
WQ Output Selected Increments= 0
WQ Output face flow=0
WQ Output face velocity=0
WQ Output face area=0
WQ Output face dispersion=0
WQ Output cell volume=0
WQ Output cell surface area=0
WQ Output cell continuity=0
WQ Output cumulative cell continuity=0
WQ Output face conc=0
WQ Output face dconc_dx=0
WQ Output face courant=0
WQ Output face peclet=0
WQ Output face adv mass=0
WQ Output face disp mass=0
WQ Output cell mass=0
WQ Output cell source sink temp=0
WQ Output cell source sink nsm=0
WQ Output MaxMinRange=-1
WQ Daily Max Min Mean=-1
WQ Daily Range=0
WQ Daily Time=0
WQ Create Restart=0
WQ Fixed Restart=0
WQ System Summary=0
WQ Use Fixed Temperature=0
Sorting and Armoring Iterations= 10
XS Update Threshold= 0.02
Hydraulics Update Threshold= 0.02
Energy Slope Method= 1
Volume Change Method= 0
XS Weighting Method= 0
Number of US Weighted Cross Sections= 1
Number of DS Weighted Cross Sections= 1
Upstream XS Weight=0.25
Main XS Weight=0.5
Downstream XS Weight=0.25
Number of DS XS's Weighted with US Boundary= 1
Upstream Boundary Weight= 1
Weight of XSs Associated with US Boundary= 0
Number of US XS's Weighted with DS Boundary= 1
Downstream Boundary Weight= 0.5
Weight of XSs Associated with DS Boundary= 0.5
Sediment Output Level= 4
Mass or Volume Output= 0
Output Increment Type= 1
Profile and TS Output Increment= 10
XS Output Flag= 0
XS Output Increment= 10
Disregard all LS=0
Disregard all Conn=0
Disregard all Breaches=0
Disregard all Pumps=0

--- Elm 01 22.f01 (steady flow) ---

Flow Title=Multiple
Number of Profiles=7
Profile Names=10-year,25-year,50-year,1pct_min,100-year,1pct_plu,500-year
River Rch & RM= Elm 01 22,Reach-1,20132
     449     657     840     666    1070    1470    1750
River Rch & RM= Elm 01 22,Reach-1,16166
     626     932    1200     962    1540    2120    2570
River Rch & RM= Elm 01 22,Reach-1,10220
     743    1110    1440    1160    1860    2560    3120
River Rch & RM= Elm 01 22,Reach-1,8346
     766    1140    1470    1180    1890    2600    3140
Boundary for River Rch & Prof#=Elm 01 22,Reach-1,1
Up Type=0
Dn Type=3
Dn Slope=0.01
Boundary for River Rch & Prof#=Elm 01 22,Reach-1,2
Up Type=0
Dn Type=3
Dn Slope=0.01
Boundary for River Rch & Prof#=Elm 01 22,Reach-1,3
Up Type=0
Dn Type=3
Dn Slope=0.01
Boundary for River Rch & Prof#=Elm 01 22,Reach-1,4
Up Type=0
Dn Type=3
Dn Slope=0.01
Boundary for River Rch & Prof#=Elm 01 22,Reach-1,5
Up Type=0
Dn Type=3
Dn Slope=0.01
Boundary for River Rch & Prof#=Elm 01 22,Reach-1,6
Up Type=0
Dn Type=3
Dn Slope=0.01
Boundary for River Rch & Prof#=Elm 01 22,Reach-1,7
Up Type=0
Dn Type=3
Dn Slope=0.01

--- Elm 01 22.g01 (geometry) ---

Geom Title=Existing Conditions
Program Version=4.10

River Reach=Elm 01 22       ,Reach-1
Reach XY= 30
        1522405.        6800788.      1524210.93      6801635.76
      1525061.73      6801647.15        1525805.        6802288.
      1526191.37      6803074.54      1527756.43      6803984.99
      1528041.77      6803974.33      1528068.36      6804301.34
       1528553.8       6804648.5       1528354.6      6806260.87
      1528560.17      6806733.41      1529753.54      6806541.52
       1529897.5        6806738.       1529706.2      6807098.51
      1529781.29      6807365.77      1530249.47      6807290.37
      1530348.49      6807630.27      1531091.52      6807824.24
      1531107.84      6808179.99      1531305.49      6808260.79
      1531108.53      6808736.55      1531356.46        6808985.
      1531594.53      6808928.16       1531462.5      6809141.14
      1531854.45      6809748.74      1531508.36      6810086.75
      1531975.08      6810207.28        1532048.      6810578.93
        1532415.      6810498.05        1532455.        6810838.

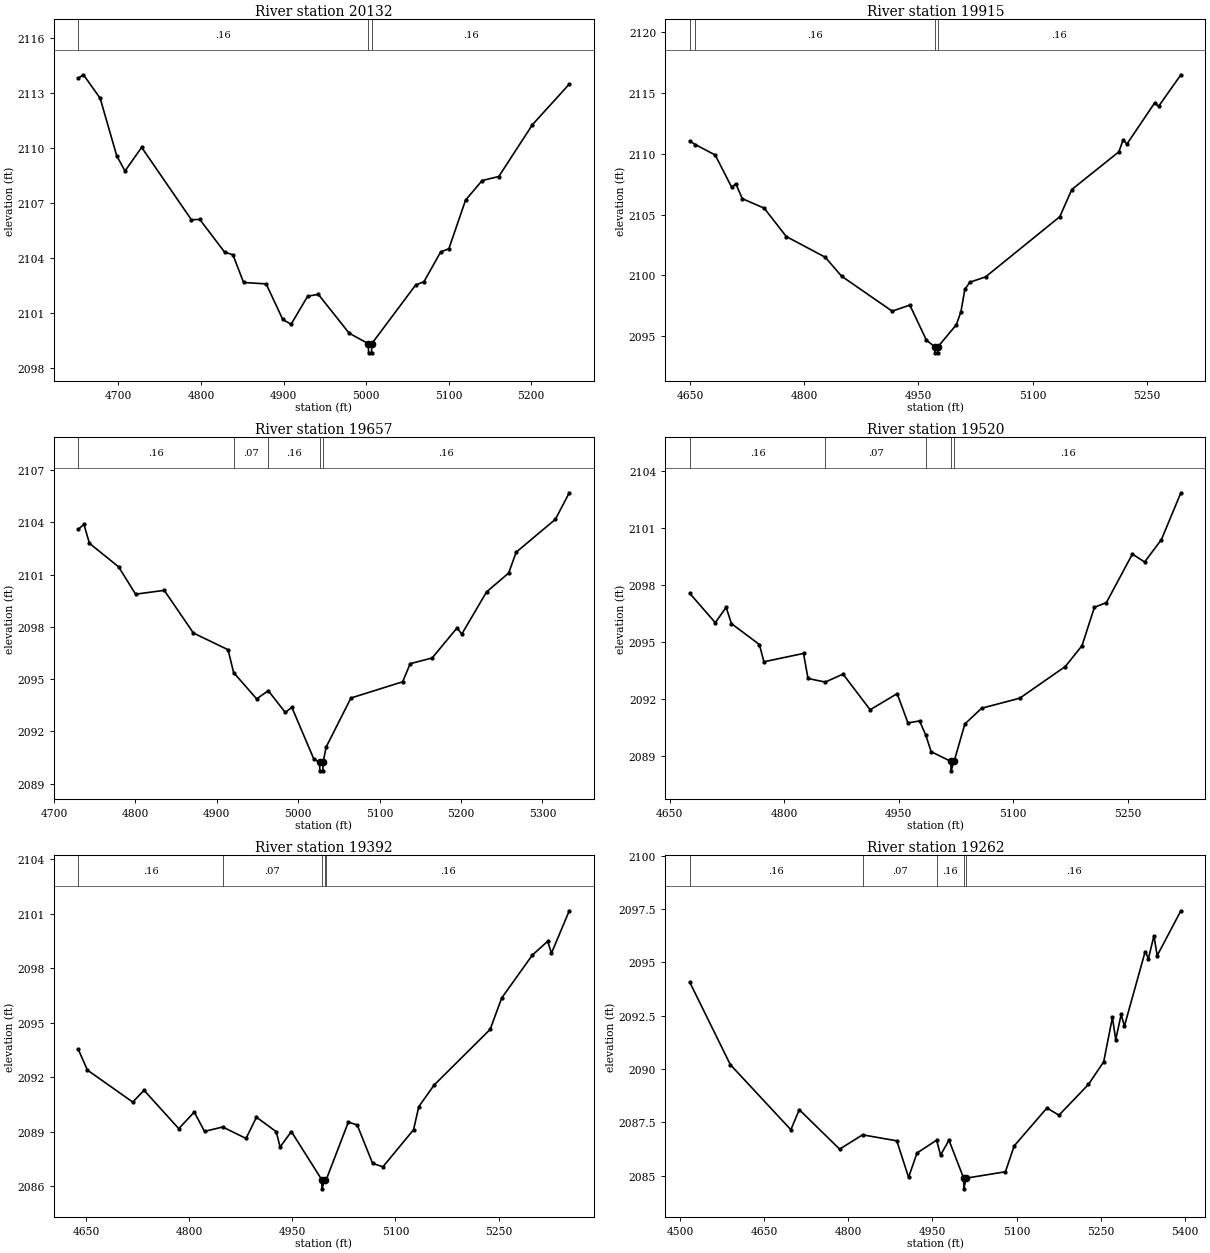
Type RM Length L Ch R = 1 ,20132   ,217,217,217
BEGIN DESCRIPTION:
Elm 01 22 20132.25
END DESCRIPTION:
XS GIS Cut Line= 3
      1522518.12      6801134.29      1522557.18      6800782.77
      1522585.83      6800543.16
#Sta/Elev= 30
  4651.3  2113.8  4657.6 2113.98  4677.8  2112.7  4697.9 2109.56  4707.9 2108.73
  4728.1 2110.02  4788.4 2106.07  4798.5 2106.09  4828.7  2104.3  4838.7 2104.16
  4851.6 2102.65    4879 2102.57  4899.1 2100.63  4909.2 2100.37  4929.3  2101.9
  4942.2    2102  4979.6 2099.88  5002.8 2099.31  5003.1 2098.81  5006.7 2098.81
    5007 2099.31  5060.1 2102.51  5070.2 2102.69  5090.4 2104.31  5100.4 2104.49
  5120.6 2107.14  5140.7 2108.21  5160.9 2108.43  5201.7 2111.26  5246.3 2113.47
#Mann= 3 ,-1 , 0
  4651.3     .16       0  5002.8     .07       0    5007     .16       0
Bank Sta=5002.8,5007
XS Rating Curve= 0 ,0
Exp/Cntr=0.3,0.1

Type RM Length L Ch R = 1 ,19915   ,258,258,258
BEGIN DESCRIPTION:
Elm 01 22 19914.67
END DESCRIPTION:
XS GIS Cut Line= 3
      1522580.63      6801147.33       1522757.7      6800845.27
      1522828.01      6800558.81
#Sta/Elev= 30
  4649.7 2111.04  4656.8 2110.76    4683  2109.9  4704.4 2107.27  4710.2 2107.52
  4718.5 2106.31  4747.4 2105.52  4776.4 2103.19  4827.5 2101.49    4849 2099.93
  4915.5 2097.05  4938.7 2097.55  4960.5 2094.66  4971.4 2094.12  4971.6 2093.62
  4975.3 2093.62  4975.6 2094.12  4999.8 2095.93  5005.8 2096.99    5011 2098.85
  5017.6 2099.43  5038.2 2099.87  5135.7 2104.82  5151.5 2107.06  5213.3 2110.16
  5218.8 2111.11    5224 2110.81  5260.4 2114.19  5265.5  2113.9  5294.8  2116.5
#Mann= 4 ,-1 , 0
  4649.7     .07       0  4656.8     .16       0  4971.4     .07       0
  4975.6     .16       0
Bank Sta=4971.4,4975.6
XS Rating Curve= 0 ,0
Exp/Cntr=0.3,0.1

Type RM Length L Ch R = 1 ,19657   ,137,137,137
BEGIN DESCRIPTION:
Elm 01 22 19656.7
END DESCRIPTION:
XS GIS Cut Line= 3
      1522762.94      6801225.45      1522937.39      6801032.77
      1523122.31      6800743.67
#Sta/Elev= 30
  4729.9  2103.6  4736.8 2103.89  4743.6  2102.8  4779.4 2101.45  4800.3 2099.88
  4835.5  2100.1  4871.3 2097.65  4913.9 2096.69  4920.7 2095.38    4949 2093.87
  4963.3 2094.34  4984.2 2093.09  4992.2 2093.39  5019.2 2090.42  5026.3 2090.24
  5026.6 2089.74  5030.3 2089.74  5030.6 2090.24  5034.4 2091.11  5064.8 2093.92
  5128.3 2094.85  5137.6 2095.89  5164.6 2096.22  5195.1 2097.94    5201 2097.59
  5231.4 2100.01  5258.5 2101.09  5267.8 2102.29    5316 2104.18    5333  2105.7
#Mann= 5 ,-1 , 0
  4729.9     .16       0  4920.7     .07       0  4963.3     .16       0
  5026.3     .07       0  5030.6     .16       0
Bank Sta=5026.3,5030.6
XS Rating Curve= 0 ,0
Exp/Cntr=0.3,0.1

Type RM Length L Ch R = 1 ,19520   ,128,128,128
BEGIN DESCRIPTION:
Elm 01 22 19519.89
END DESCRIPTION:
XS GIS Cut Line= 3
      1522890.51      6801358.29      1523059.78      6801087.46
      1523212.89        6800802.
#Sta/Elev= 30
  4676.6 2097.55  4709.9 2096.01  4724.1 2096.82  4731.1 2095.96  4767.7 2094.86
  4773.6 2093.95  4825.5 2094.39  4831.4 2093.07    4854 2092.88  4877.3  2093.3
  4912.8 2091.42  4948.2 2092.27  4962.3 2090.73  4977.6 2090.83  4985.8 2090.07
  4992.7 2089.21  5018.5  2088.7  5018.8  2088.2  5022.8  2088.7  5036.9 2090.67
  5058.8  2091.5  5108.8 2092.03  5168.5  2093.7  5190.4  2094.8  5206.6 2096.82
  5222.3 2097.07  5256.4 2099.63  5272.4 2099.21  5294.4 2100.39  5319.9 2102.86
#Mann= 5 ,-1 , 0
  4676.6     .16       0    4854     .07       0  4985.8     .16       0
  5018.5     .07       0  5022.8     .16       0
Bank Sta=5018.5,5022.8
XS Rating Curve= 0 ,0
Exp/Cntr=0.3,0.1

Type RM Length L Ch R = 1 ,19392   ,130,130,130
BEGIN DESCRIPTION:
Elm 01 22 19391.85
END DESCRIPTION:
XS GIS Cut Line= 3
      1523005.09      6801457.25      1523171.76      6801142.15
      1523332.92      6800822.43
#Sta/Elev= 30
  4638.4 2093.54  4651.7  2092.4  4717.7 2090.64  4734.1 2091.29  4784.6 2089.18
  4807.2 2090.09  4822.1 2089.03  4848.6 2089.27  4882.5 2088.64  4897.7 2089.81
  4926.5 2089.01  4932.1 2088.17  4948.5 2089.02  4992.7 2086.37    4993 2085.87
    4997 2086.37  4999.2 2086.37  5031.4 2089.54  5044.3 2089.38  5066.7 2087.27
  5081.7 2087.08  5126.3 2089.12  5133.9 2090.39  5156.3 2091.58  5237.8 2094.64
  5254.5 2096.36  5299.1 2098.72  5321.4 2099.48    5327 2098.83  5352.9 2101.16
#Mann= 5 ,-1 , 0
  4638.4     .16       0  4848.6     .07       0  4992.7     .07       0
    4997     .07       0  4999.2     .16       0
Bank Sta=4992.7,4997
XS Rating Curve= 0 ,0
Exp/Cntr=0.3,0.1

Type RM Length L Ch R = 1 ,19262   ,117,117,117
BEGIN DESCRIPTION:
Elm 01 22 19262.22
END DESCRIPTION:
XS GIS Cut Line= 3
      1523020.73      6801574.42      1523291.55       6801173.4
      1523492.05      6800837.49
#Sta/Elev= 30
  4517.8 2094.05  4589.9  2090.2  4697.8 2087.15  4712.8 2088.09  4784.7 2086.24
  4825.5 2086.91  4886.6 2086.63  4907.6 2084.92  4922.6 2086.06  4957.6 2086.66
  4964.6 2085.96  4979.6 2086.66  5005.8 2084.88  5006.1 2084.38  5010.1 2084.88
  5080.2 2085.18  5095.8 2086.39  5154.2 2088.17  5175.6 2087.83  5228.1 2089.27
  5255.3 2090.33  5270.9 2092.41  5276.8 2091.37  5286.5 2092.55  5292.3 2092.01
  5329.3  2095.5  5335.1 2095.17  5344.9 2096.24  5350.7 2095.31  5392.9 2097.41
#Mann= 5 ,-1 , 0
  4517.8     .16       0  4825.5     .07       0  4957.6     .16       0
  5005.8     .07       0  5010.1     .16       0
Bank Sta=5005.8,5010.1
XS Rating Curve= 0 ,0
Exp/Cntr=0.3,0.1

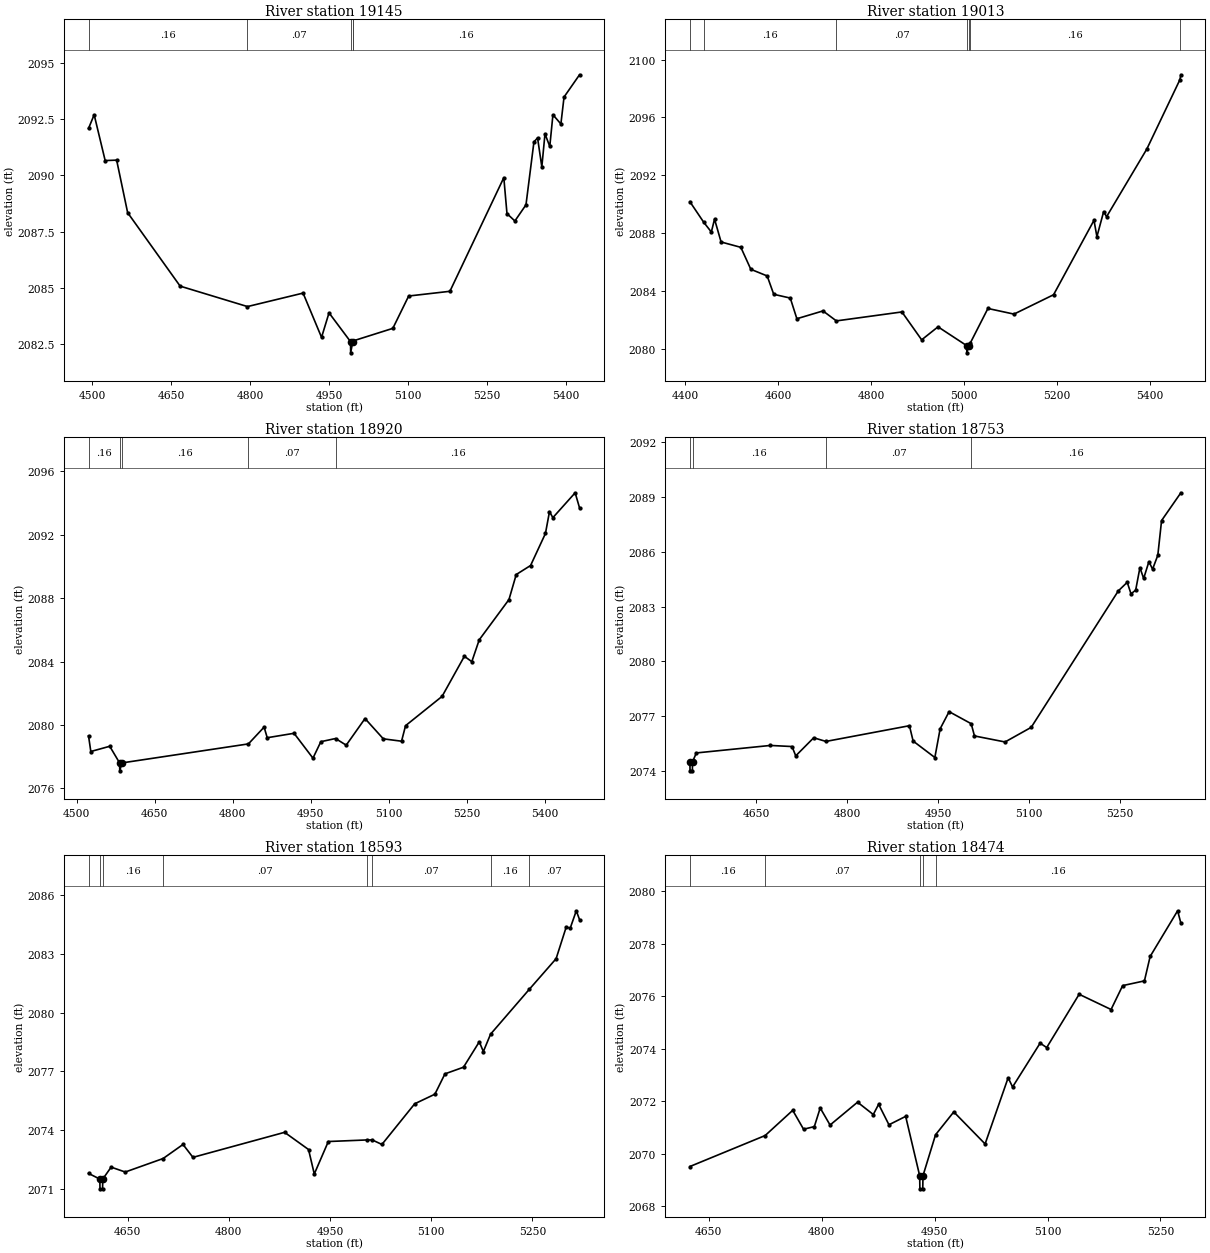
Type RM Length L Ch R = 1 ,19145   ,132,132,132
BEGIN DESCRIPTION:
Elm 01 22 19145.34
END DESCRIPTION:
XS GIS Cut Line= 3
      1523041.58      6801639.52      1523367.07      6801267.15
      1523608.25       6800901.5
#Sta/Elev= 30
    4493 2092.09  4503.7  2092.7  4524.6 2090.66  4546.4 2090.68  4567.3 2088.34
    4667 2085.07  4794.9 2084.16  4900.5 2084.76  4935.6 2082.79  4949.8 2083.88
  4990.6  2082.6  4990.9  2082.1  4994.9  2082.6  4995.4 2082.63    5071 2083.19
  5101.1 2084.63  5179.4 2084.84  5281.8  2089.9  5287.8  2088.3  5302.8 2087.97
  5323.9 2088.69    5339 2091.49  5345.9 2091.67    5354 2090.38    5360 2091.85
  5369.1 2091.29  5375.1  2092.7  5390.2 2092.29  5396.2 2093.49  5425.6 2094.48
#Mann= 5 ,-1 , 0
    4493     .16       0  4794.9     .07       0  4990.6     .07       0
  4994.9     .07       0  4995.4     .16       0
Bank Sta=4990.6,4994.9
XS Rating Curve= 0 ,0
Exp/Cntr=0.3,0.1

Type RM Length L Ch R = 1 ,19013   ,93,93,93
BEGIN DESCRIPTION:
Elm 01 22 19012.78
END DESCRIPTION:
XS GIS Cut Line= 3
      1523057.19      6801725.47      1523481.66      6801324.44
      1523770.34      6800949.93
#Sta/Elev= 30
  4409.6 2090.17  4439.3 2088.75  4455.8 2088.07  4462.7 2088.96  4476.8 2087.38
  4519.3 2087.01  4540.8 2085.49    4576 2085.03  4590.1 2083.76  4625.7  2083.5
  4639.9 2082.07  4696.1 2082.61  4724.9 2081.92    4866 2082.54  4908.5 2080.61
  4943.7 2081.51  5005.4 2080.21  5005.7 2079.71  5009.8 2080.21  5012.9 2080.37
  5051.1 2082.78  5107.2 2082.39  5192.4 2083.73  5279.4 2088.88  5285.7 2087.75
  5300.2 2089.48  5306.5 2089.13  5393.1 2093.81  5464.2  2098.6  5466.4 2098.95
#Mann= 7 ,-1 , 0
  4409.6     .07       0  4439.3     .16       0  4724.9     .07       0
  5005.4     .07       0  5009.8     .07       0  5012.9     .16       0
  5464.2     .07       0
Bank Sta=5005.4,5009.8
XS Rating Curve= 0 ,0
Exp/Cntr=0.3,0.1

Type RM Length L Ch R = 1 ,18920   ,167,167,167
BEGIN DESCRIPTION:
Elm 01 22 18920.01
END DESCRIPTION:
XS GIS Cut Line= 3
      1523296.76      6801785.39      1523557.18      6801376.52
      1523854.05      6801024.96
#Sta/Elev= 30
  4522.5 2079.31  4526.9 2078.32  4563.3 2078.65  4582.3  2077.6  4582.6  2077.1
  4586.7  2077.6  4830.2  2078.8  4860.4 2079.86  4866.4 2079.19    4918 2079.47
  4954.4  2077.9  4969.6 2078.94  4997.9 2079.14  5018.4 2078.72  5054.6  2080.4
  5089.8 2079.12  5124.9 2078.97  5132.6 2079.95  5202.9  2081.8  5245.8 2084.33
  5260.1 2083.99  5274.4 2085.37  5331.6 2087.91  5345.6 2089.49  5373.2 2090.06
  5401.8 2092.08  5409.6 2093.46  5416.1 2093.08    5459 2094.65  5467.4  2093.7
#Mann= 5 ,-1 , 0
  4522.5     .16       0  4582.3     .07       0  4586.7     .16       0
  4830.2     .07       0  4997.9     .16       0
Bank Sta=4582.3,4586.7
XS Rating Curve= 0 ,0
Exp/Cntr=0.3,0.1

Type RM Length L Ch R = 1 ,18753   ,160,160,160
BEGIN DESCRIPTION:
Elm 01 22 18753.22
END DESCRIPTION:
XS GIS Cut Line= 3
      1523441.31      6801808.05      1523705.61      6801431.21
      1523908.72      6801147.38
#Sta/Elev= 30
  4541.1 2074.51  4541.4 2074.01  4545.2 2074.01  4545.5 2074.51  4551.8 2074.99
  4673.8  2075.4  4709.5 2075.34  4715.6 2074.83  4745.2 2075.82  4765.4 2075.62
    4903 2076.48  4909.1 2075.64  4944.9 2074.74  4953.6 2076.31  4968.4 2077.25
  5004.8 2076.59  5010.2 2075.92  5060.6 2075.59  5103.7 2076.39  5247.3 2083.86
    5262 2084.33  5268.2  2083.7  5275.9  2083.9  5282.9 2085.13  5289.1 2084.54
  5297.7 2085.46  5303.8 2085.05  5312.4 2085.81  5318.6 2087.71  5350.4 2089.23
#Mann= 4 ,-1 , 0
  4541.1     .07       0  4545.5     .16       0  4765.4     .07       0
  5004.8     .16       0
Bank Sta=4541.1,4545.5
XS Rating Curve= 0 ,0
Exp/Cntr=0.3,0.1

Type RM Length L Ch R = 1 ,18593   ,119,119,119
BEGIN DESCRIPTION:
Elm 01 22 18592.6
END DESCRIPTION:
XS GIS Cut Line= 3
      1523609.26      6801808.81      1523854.05      6801475.48
      1524030.59      6801215.88
#Sta/Elev= 30
  4592.2 2071.78  4608.9 2071.49  4609.2 2070.99    4613 2070.99  4613.3 2071.49
  4625.7  2072.1  4646.6 2071.85  4702.7 2072.54  4732.2 2073.26  4746.9  2072.6
  4882.7 2073.88  4918.2    2073  4926.7 2071.75  4947.5 2073.41  5004.3 2073.49
  5012.6 2073.49  5026.9 2073.26  5075.5 2075.34  5105.4 2075.83  5120.3 2076.87
  5147.8 2077.21  5171.2 2078.51  5177.2 2078.01  5187.9  2078.9  5245.2 2081.19
    5285 2082.76  5299.9 2084.37    5306 2084.33  5314.9 2085.21  5319.7 2084.76
#Mann= 8 ,-1 , 0
  4592.2     .16       0  4608.9     .07       0  4613.3     .16       0
  4702.7     .07       0  5004.3     .16       0  5012.6     .07       0
  5187.9     .16       0  5245.2     .07       0
Bank Sta=4608.9,4613.3
XS Rating Curve= 0 ,0
Exp/Cntr=0.3,0.1

Type RM Length L Ch R = 1 ,18474   ,123,123,123
BEGIN DESCRIPTION:
Elm 01 22 18474.27
END DESCRIPTION:
XS GIS Cut Line= 3
      1523716.01      6801821.87      1523953.01      6801532.77
      1524100.73      6801296.95
#Sta/Elev= 30
    4625 2069.52    4725  2070.7  4761.6 2071.66    4776 2070.94  4790.3 2071.04
  4798.1 2071.75  4811.2  2071.1  4847.7 2071.97  4868.6  2071.5  4875.7 2071.89
  4889.4 2071.11  4911.6 2071.43  4930.2 2069.17  4930.5 2068.67  4934.3 2068.67
  4934.6 2069.17  4951.3 2070.73  4975.5  2071.6  5017.1 2070.38  5047.7  2072.9
  5053.6 2072.55  5090.2 2074.22  5098.9 2074.05    5142 2076.08  5184.4  2075.5
  5199.8 2076.41  5228.7 2076.59  5236.3 2077.52  5272.8 2079.26  5277.1 2078.79
#Mann= 5 ,-1 , 0
    4625     .16       0    4725     .07       0  4930.2     .07       0
  4934.6     .07       0  4951.3     .16       0
Bank Sta=4930.2,4934.6
XS Rating Curve= 0 ,0
Exp/Cntr=0.3,0.1

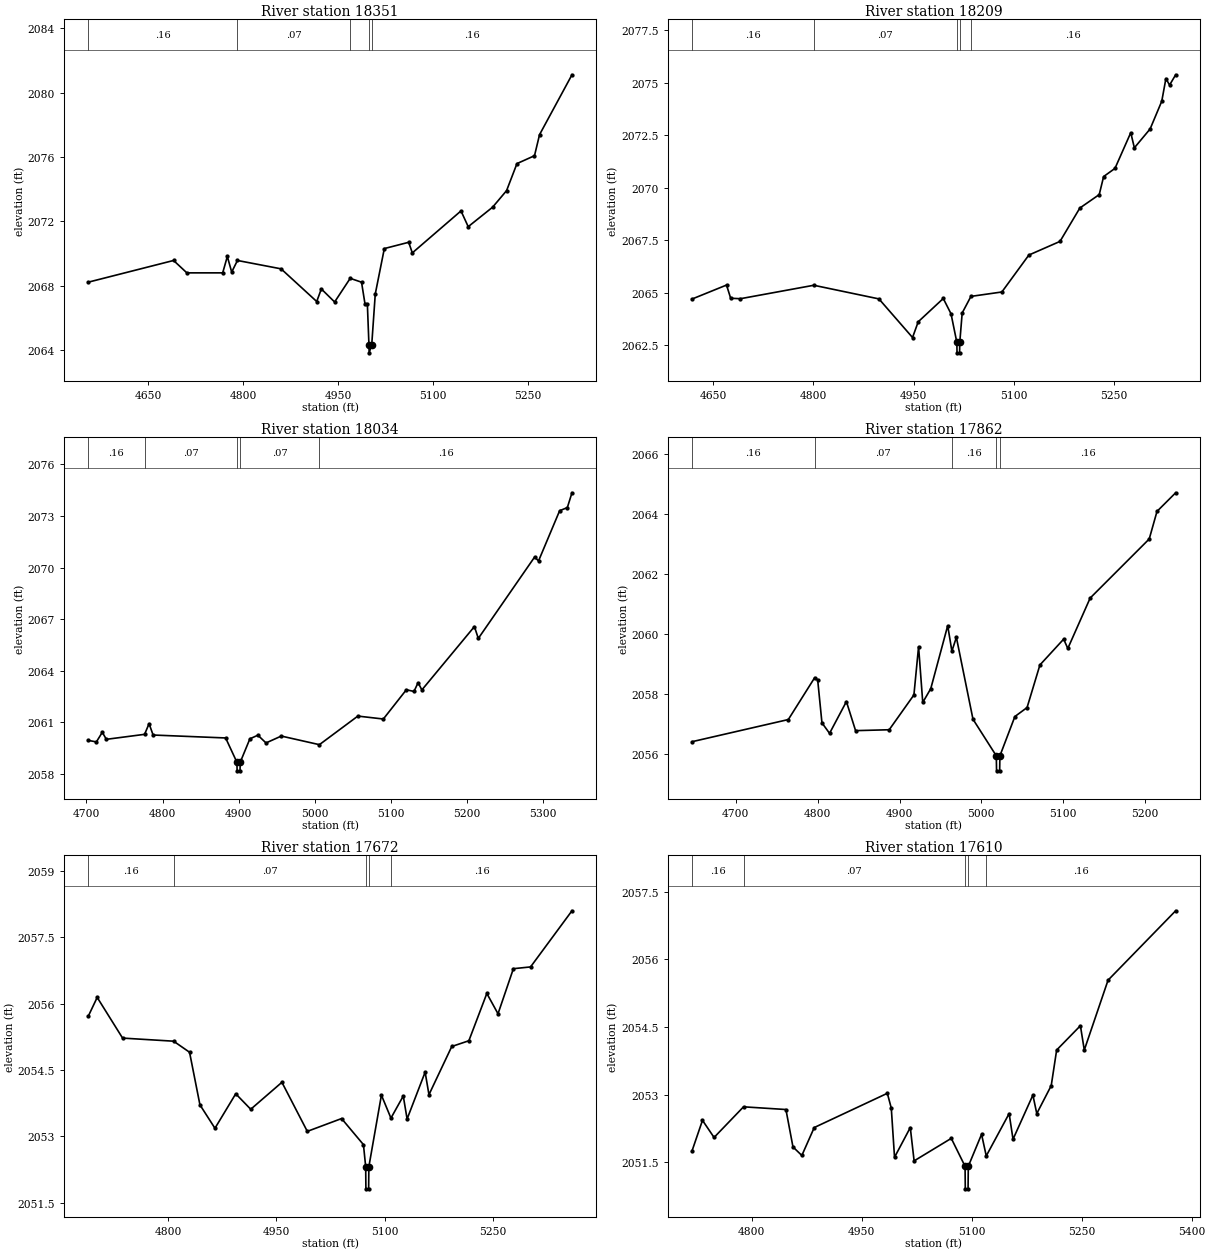
Type RM Length L Ch R = 1 ,18351   ,142,142,142
BEGIN DESCRIPTION:
Elm 01 22 18350.86
END DESCRIPTION:
XS GIS Cut Line= 3
      1523765.52      6801879.12      1524067.59      6801561.42
      1524218.48      6801272.65
#Sta/Elev= 30
  4555.2 2068.22  4690.1 2069.57  4711.1  2068.8  4767.7  2068.8    4775 2069.82
  4781.9 2068.85    4791 2069.57  4859.9 2069.05  4916.2 2067.02  4923.5  2067.8
  4944.5 2066.99  4969.1 2068.46    4987 2068.22  4992.5 2066.86  4996.2 2066.86
  4998.7 2064.33    4999 2063.83  5003.1 2064.33  5008.7 2067.49    5023 2070.31
  5061.5  2070.7  5067.2 2070.04  5144.1 2072.65  5155.5 2071.67    5194 2072.88
  5216.1 2073.91  5232.5 2075.59  5260.2 2076.08  5268.2 2077.39  5319.4 2081.11
#Mann= 5 ,-1 , 0
  4555.2     .16       0    4791     .07       0  4969.1     .16       0
  4998.7     .07       0  5003.1     .16       0
Bank Sta=4998.7,5003.1
XS Rating Curve= 0 ,0
Exp/Cntr=0.3,0.1

Type RM Length L Ch R = 1 ,18209   ,175,175,175
BEGIN DESCRIPTION:
Elm 01 22 18208.92
END DESCRIPTION:
XS GIS Cut Line= 3
      1523968.65      6801933.79      1524187.39      6801631.73
       1524325.4      6801308.83
#Sta/Elev= 30
    4618 2064.69  4669.9 2065.36  4676.1 2064.73  4690.8 2064.71  4800.5 2065.35
    4898  2064.7  4948.3 2062.86  4956.8 2063.61  4994.3 2064.72  5005.9 2063.99
  5014.6 2062.63  5014.9 2062.13  5018.7 2062.13    5019 2062.63  5022.6 2064.03
  5035.7 2064.82    5082 2065.03  5122.4 2066.79    5169 2067.44  5198.7 2069.03
  5227.7 2069.67  5234.3 2070.53  5251.3 2070.92  5274.9 2072.62  5280.3  2071.9
  5303.9  2072.8  5321.3 2074.12  5327.5  2075.2    5333 2074.89  5342.1 2075.38
#Mann= 5 ,-1 , 0
    4618     .16       0  4800.5     .07       0  5014.6     .07       0
    5019     .07       0  5035.7     .16       0
Bank Sta=5014.6,5019
XS Rating Curve= 0 ,0
Exp/Cntr=0.3,0.1

Type RM Length L Ch R = 1 ,18034   ,172,172,172
BEGIN DESCRIPTION:
Elm 01 22 18033.68
END DESCRIPTION:
XS GIS Cut Line= 3
       1524262.9      6801918.21      1524361.86      6801642.15
      1524406.01      6801301.97
#Sta/Elev= 30
  4702.2 2059.96    4713 2059.87  4720.8 2060.43  4726.1 2060.02  4776.4 2060.31
  4782.3 2060.93  4787.6 2060.27    4883  2060.1  4897.8 2058.69  4898.1 2058.19
  4901.9 2058.19  4902.2 2058.69  4914.9 2060.05  4925.4 2060.26  4936.1 2059.81
  4956.2 2060.21  5006.3 2059.71  5056.9 2061.37  5090.4  2061.2  5120.7  2062.9
  5130.7  2062.8  5136.1 2063.31  5141.1 2062.89  5210.2 2066.57  5215.3 2065.88
  5289.4 2070.61  5294.5 2070.38  5322.3  2073.3  5332.4 2073.48  5338.5 2074.34
#Mann= 5 ,-1 , 0
  4702.2     .16       0  4776.4     .07       0  4897.8     .07       0
  4902.2     .07       0  5006.3     .16       0
Bank Sta=4897.8,4902.2
XS Rating Curve= 0 ,0
Exp/Cntr=0.3,0.1

Type RM Length L Ch R = 1 ,17862   ,190,190,190
BEGIN DESCRIPTION:
Elm 01 22 17861.93
END DESCRIPTION:
XS GIS Cut Line= 3
      1524432.18      6801931.19      1524518.11      6801590.07
      1524567.59      6801355.71
#Sta/Elev= 30
  4646.2 2056.42  4764.1 2057.16  4796.4 2058.56    4800 2058.48  4805.2 2057.05
  4814.5  2056.7  4835.1 2057.76  4846.3 2056.79  4887.4 2056.82  4917.6 2057.98
  4923.3 2059.59  4928.4 2057.73  4938.2 2058.19  4958.9 2060.29    4964 2059.44
  4969.5  2059.9  4989.8 2057.17  5018.3 2055.95  5018.6 2055.45  5022.4 2055.45
  5022.7 2055.95    5041 2057.26  5055.9 2057.56  5071.6 2058.98  5100.6 2059.84
  5105.7 2059.53    5133 2061.21  5205.2 2063.18  5214.7  2064.1  5237.5 2064.72
#Mann= 5 ,-1 , 0
  4646.2     .16       0  4796.4     .07       0    4964     .16       0
  5018.3     .07       0  5022.7     .16       0
Bank Sta=5018.3,5022.7
XS Rating Curve= 0 ,0
Exp/Cntr=0.3,0.1

Type RM Length L Ch R = 1 ,17672   ,62,62,62
BEGIN DESCRIPTION:
Elm 01 22 17671.67
END DESCRIPTION:
XS GIS Cut Line= 3
      1524471.27       6801941.6      1524663.95      6801702.05
      1524791.15      6801361.98
#Sta/Elev= 30
  4689.1 2055.71  4701.6 2056.14  4736.8 2055.22  4807.5 2055.15  4829.6  2054.9
    4844 2053.71  4864.8 2053.18  4893.6 2053.96  4914.4 2053.61  4957.6 2054.22
  4992.8 2053.11  5040.3  2053.4  5070.6 2052.81  5073.7 2052.31    5074 2051.81
  5077.8 2051.81  5078.1 2052.31  5095.5 2053.93  5108.7 2053.41  5125.8 2053.91
  5131.1 2053.39  5156.1 2054.45  5161.4 2053.94    5193 2055.03  5216.7 2055.16
  5241.6 2056.23  5257.1 2055.77  5278.4 2056.79  5302.2 2056.83  5359.6  2058.1
#Mann= 5 ,-1 , 0
  4689.1     .16       0  4807.5     .07       0  5073.7     .07       0
  5078.1     .07       0  5108.7     .16       0
Bank Sta=5073.7,5078.1
XS Rating Curve= 0 ,0
Exp/Cntr=0.3,0.1

Type RM Length L Ch R = 1 ,17610   ,111,111,111
BEGIN DESCRIPTION:
Elm 01 22 17609.82
END DESCRIPTION:
XS GIS Cut Line= 3
      1524604.06      6801985.88      1524713.43      6801730.69
      1524828.01      6801366.11
#Sta/Elev= 30
  4718.3 2051.74  4732.8 2052.43  4748.6 2052.05  4788.8 2052.73  4846.6 2052.67
  4856.2 2051.84  4868.3 2051.65  4885.2 2052.27  4984.9 2053.03  4990.3  2052.7
  4994.7 2051.61  5016.2 2052.27  5021.4 2051.53  5072.1 2052.03  5090.9 2051.41
  5091.2 2050.91    5095 2050.91  5095.3 2051.41  5113.4 2052.12  5119.8 2051.64
    5151 2052.58  5156.3 2052.01  5183.4 2052.99  5188.7 2052.58  5208.4  2053.2
  5215.8 2053.99  5248.2 2054.53  5253.5 2053.99  5285.9 2055.54  5378.1 2057.08
#Mann= 5 ,-1 , 0
  4718.3     .16       0  4788.8     .07       0  5090.9     .07       0
  5095.3     .07       0  5119.8     .16       0
Bank Sta=5090.9,5095.3
XS Rating Curve= 0 ,0
Exp/Cntr=0.3,0.1

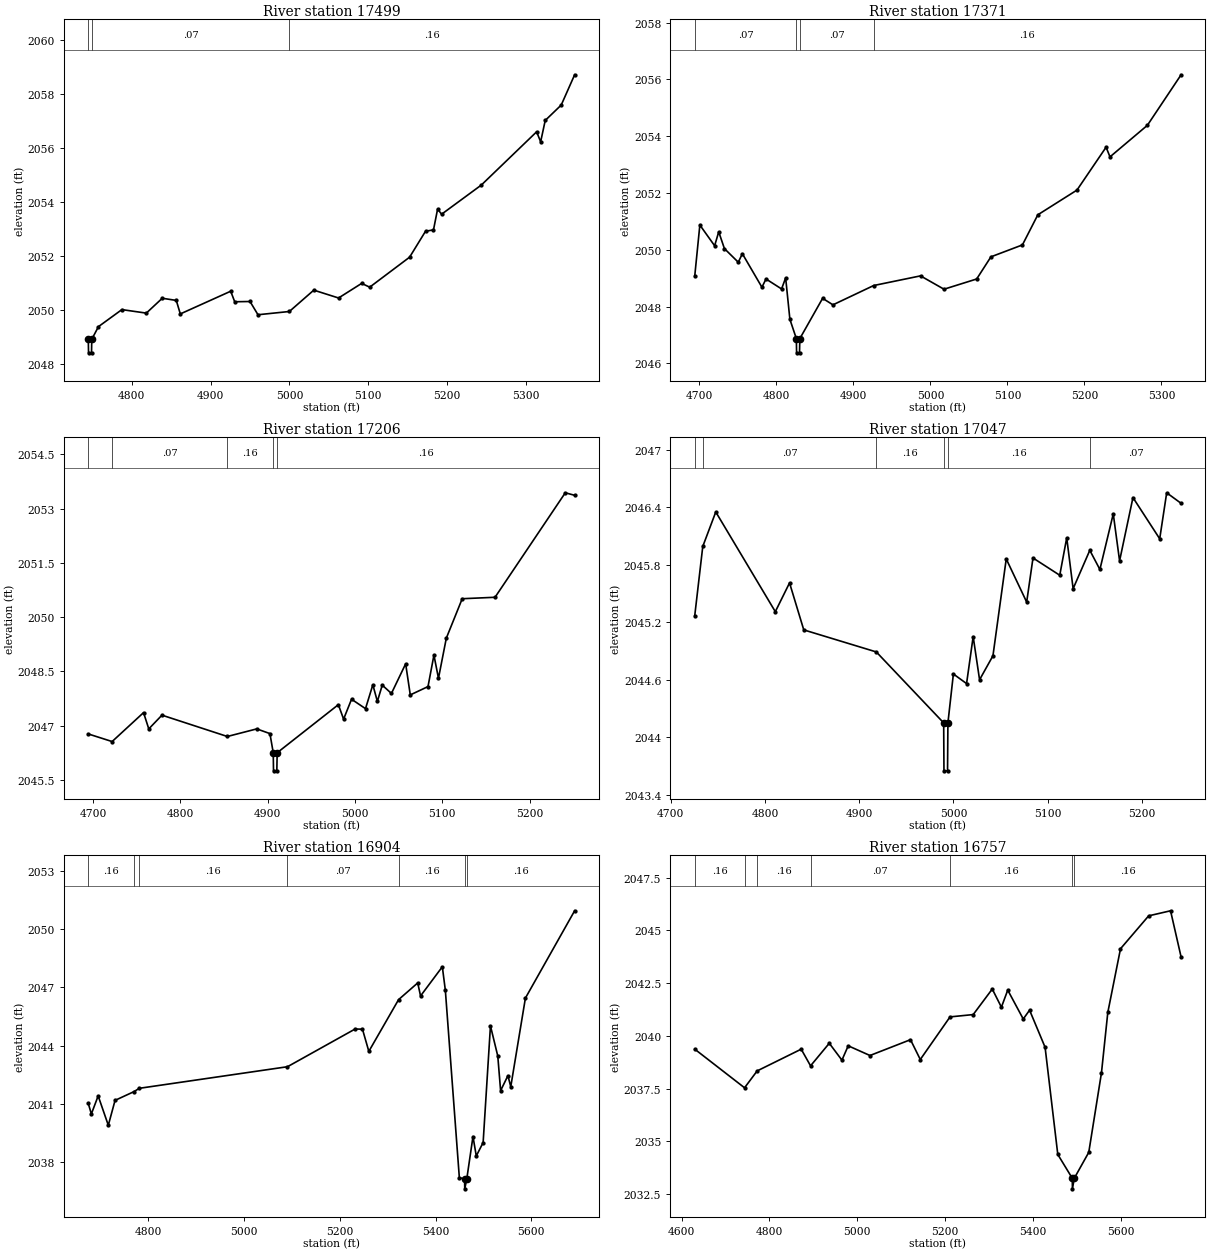
Type RM Length L Ch R = 1 ,17499   ,128,128,128
BEGIN DESCRIPTION:
Elm 01 22 17498.82
END DESCRIPTION:
XS GIS Cut Line= 3
        1524773.      6801930.79      1524809.78      6801686.42
      1524866.77      6801321.16
#Sta/Elev= 30
  4744.9 2048.93  4745.2 2048.43    4749 2048.43  4749.3 2048.93  4757.8  2049.4
  4787.5 2050.03  4818.5  2049.9  4838.7 2050.45  4856.5 2050.37  4861.6 2049.87
  4925.5 2050.71  4930.6 2050.32    4950 2050.33  4960.1 2049.84  4999.9 2049.96
  5030.9 2050.75  5062.3 2050.46  5091.6    2051  5101.8 2050.86  5152.4 2051.97
  5172.6 2052.93  5182.7 2052.98  5187.9 2053.75    5193 2053.56  5243.4 2054.64
  5313.5 2056.61  5318.6 2056.24  5324.4 2057.03  5344.7  2057.6  5361.7 2058.72
#Mann= 3 ,-1 , 0
  4744.9     .07       0  4749.3     .07       0  4999.9     .16       0
Bank Sta=4744.9,4749.3
XS Rating Curve= 0 ,0
Exp/Cntr=0.3,0.1

Type RM Length L Ch R = 1 ,17371   ,165,165,165
BEGIN DESCRIPTION:
Elm 01 22 17370.64
END DESCRIPTION:
XS GIS Cut Line= 3
       1524820.2      6801944.23      1524916.55        6801676.
      1524976.45      6801334.83
#Sta/Elev= 30
  4694.1 2049.08  4700.7 2050.87  4719.9 2050.14  4725.2 2050.63  4732.6 2050.04
  4750.6 2049.56  4755.9 2049.86  4781.3 2048.68  4786.6 2048.97  4806.8 2048.62
  4812.1 2049.01  4817.6 2047.55    4826 2046.87  4826.3 2046.37  4830.1 2046.37
  4830.5 2046.87  4860.1 2048.29  4873.5 2048.06  4926.4 2048.74  4987.2 2049.08
  5017.7 2048.61  5060.1 2048.97  5078.6 2049.75  5119.5 2050.17  5139.5 2051.23
  5190.3  2052.1  5228.1 2053.61  5233.2 2053.27  5281.7 2054.38  5325.5 2056.16
#Mann= 4 ,-1 , 0
  4694.1     .07       0    4826     .07       0  4830.5     .07       0
  4926.4     .16       0
Bank Sta=4826,4830.5
XS Rating Curve= 0 ,0
Exp/Cntr=0.3,0.1

Type RM Length L Ch R = 1 ,17206   ,159,159,159
BEGIN DESCRIPTION:
Elm 01 22 17206.09
END DESCRIPTION:
XS GIS Cut Line= 3
      1524893.11      6801902.58      1525064.99      6801639.55
      1525137.91      6801407.76
#Sta/Elev= 30
  4694.4 2046.77  4721.7 2046.56  4757.7 2047.36  4763.7 2046.91  4778.8 2047.29
  4853.7  2046.7  4887.4 2046.91  4902.5 2046.78  4906.3 2046.25  4906.6 2045.75
  4910.4 2045.75  4910.8 2046.25  4980.9 2047.58  4986.9 2047.18    4996 2047.73
    5012 2047.47  5020.4 2048.13  5025.6 2047.67  5031.2 2048.12  5041.7 2047.89
    5058 2048.71  5063.3 2047.85  5083.6 2048.08  5090.4 2048.95  5095.6 2048.31
  5104.6 2049.42  5122.8 2050.51  5160.4 2050.55  5240.9 2053.44  5251.6 2053.37
#Mann= 5 ,-1 , 0
  4694.4     .16       0  4721.7     .07       0  4853.7     .16       0
  4906.3     .07       0  4910.8     .16       0
Bank Sta=4906.3,4910.8
XS Rating Curve= 0 ,0
Exp/Cntr=0.3,0.1

Type RM Length L Ch R = 1 ,17047   ,143,143,143
BEGIN DESCRIPTION:
Elm 01 22 17046.64
END DESCRIPTION:
XS GIS Cut Line= 3
      1524945.21      6801907.77      1525179.57      6801754.13
      1525338.43      6801579.64
#Sta/Elev= 30
  4725.4 2045.27  4733.9 2045.99  4747.7 2046.35  4810.9 2045.31    4826 2045.61
  4841.1 2045.12  4918.1 2044.89  4989.6 2044.15  4989.9 2043.65  4993.7 2043.65
  4994.1 2044.15  4999.9 2044.66  5013.9 2044.56  5020.9 2045.05  5027.7  2044.6
  5041.9 2044.85    5056 2045.86  5077.7 2045.41  5084.4 2045.87  5112.8 2045.69
  5120.2 2046.08    5127 2045.55  5144.7 2045.95  5155.4 2045.75  5169.6 2046.33
  5176.3 2045.84  5190.5  2046.5  5218.9 2046.07  5226.3 2046.55  5241.6 2046.44
#Mann= 6 ,-1 , 0
  4725.4     .16       0  4733.9     .07       0  4918.1     .16       0
  4989.6     .07       0  4994.1     .16       0  5144.7     .07       0
Bank Sta=4989.6,4994.1
XS Rating Curve= 0 ,0
Exp/Cntr=0.3,0.1

Type RM Length L Ch R = 1 ,16904   ,147,147,147
BEGIN DESCRIPTION:
Elm 01 22 16904.4
END DESCRIPTION:
XS GIS Cut Line= 3
      1525057.16      6802069.25      1525278.53      6801850.48
      1525653.53      6801254.12
#Sta/Elev= 30
  4674.7 2041.02  4681.1 2040.48  4695.3 2041.41  4716.5  2039.9  4730.6 2041.18
  4770.2 2041.63  4781.2  2041.8  5090.7 2042.91    5232 2044.85  5247.3 2044.84
  5260.6  2043.7  5322.7 2046.36  5362.7 2047.22  5368.6 2046.55  5414.1 2048.05
  5420.4 2046.84  5449.6 2037.21  5460.6 2037.13  5460.9 2036.63  5465.1 2037.13
  5478.1 2039.32    5485 2038.32  5499.3 2039.01  5514.6 2045.01  5529.9 2043.46
  5535.8 2041.68  5551.1 2042.45    5557 2041.88  5587.6 2046.44  5690.4 2050.93
#Mann= 7 ,-1 , 0
  4674.7     .16       0  4770.2     .07       0  4781.2     .16       0
  5090.7     .07       0  5322.7     .16       0  5460.6     .07       0
  5465.1     .16       0
Bank Sta=5460.6,5465.1
XS Rating Curve= 0 ,0
Exp/Cntr=0.3,0.1

Type RM Length L Ch R = 1 ,16757   ,106,106,106
BEGIN DESCRIPTION:
Elm 01 22 16757.43
END DESCRIPTION:
XS GIS Cut Line= 3
      1525111.83      6802165.61      1525390.51      6801939.02
      1525853.04      6801351.77
#Sta/Elev= 30
    4630 2039.37  4743.3 2037.54    4772 2038.34  4872.2 2039.37  4893.5 2038.58
  4936.1 2039.65  4964.9 2038.85  4979.2 2039.53  5028.7 2039.07  5120.9 2039.82
  5143.2 2038.88  5210.9  2040.9  5263.6 2041.01    5307 2042.22  5327.8 2041.36
  5342.2 2042.17  5377.5  2040.8  5391.9 2041.22  5427.2 2039.46  5456.1 2034.38
  5489.1 2033.25  5489.4 2032.75  5493.6 2033.25  5526.6 2034.48  5555.5 2038.25
  5569.9 2041.11  5598.8 2044.13  5662.9 2045.69  5712.7 2045.93  5736.7 2043.74
#Mann= 7 ,-1 , 0
    4630     .16       0  4743.3     .07       0    4772     .16       0
  4893.5     .07       0  5210.9     .16       0  5489.1     .07       0
  5493.6     .16       0
Bank Sta=5489.1,5493.6
XS Rating Curve= 0 ,0
Exp/Cntr=0.3,0.1

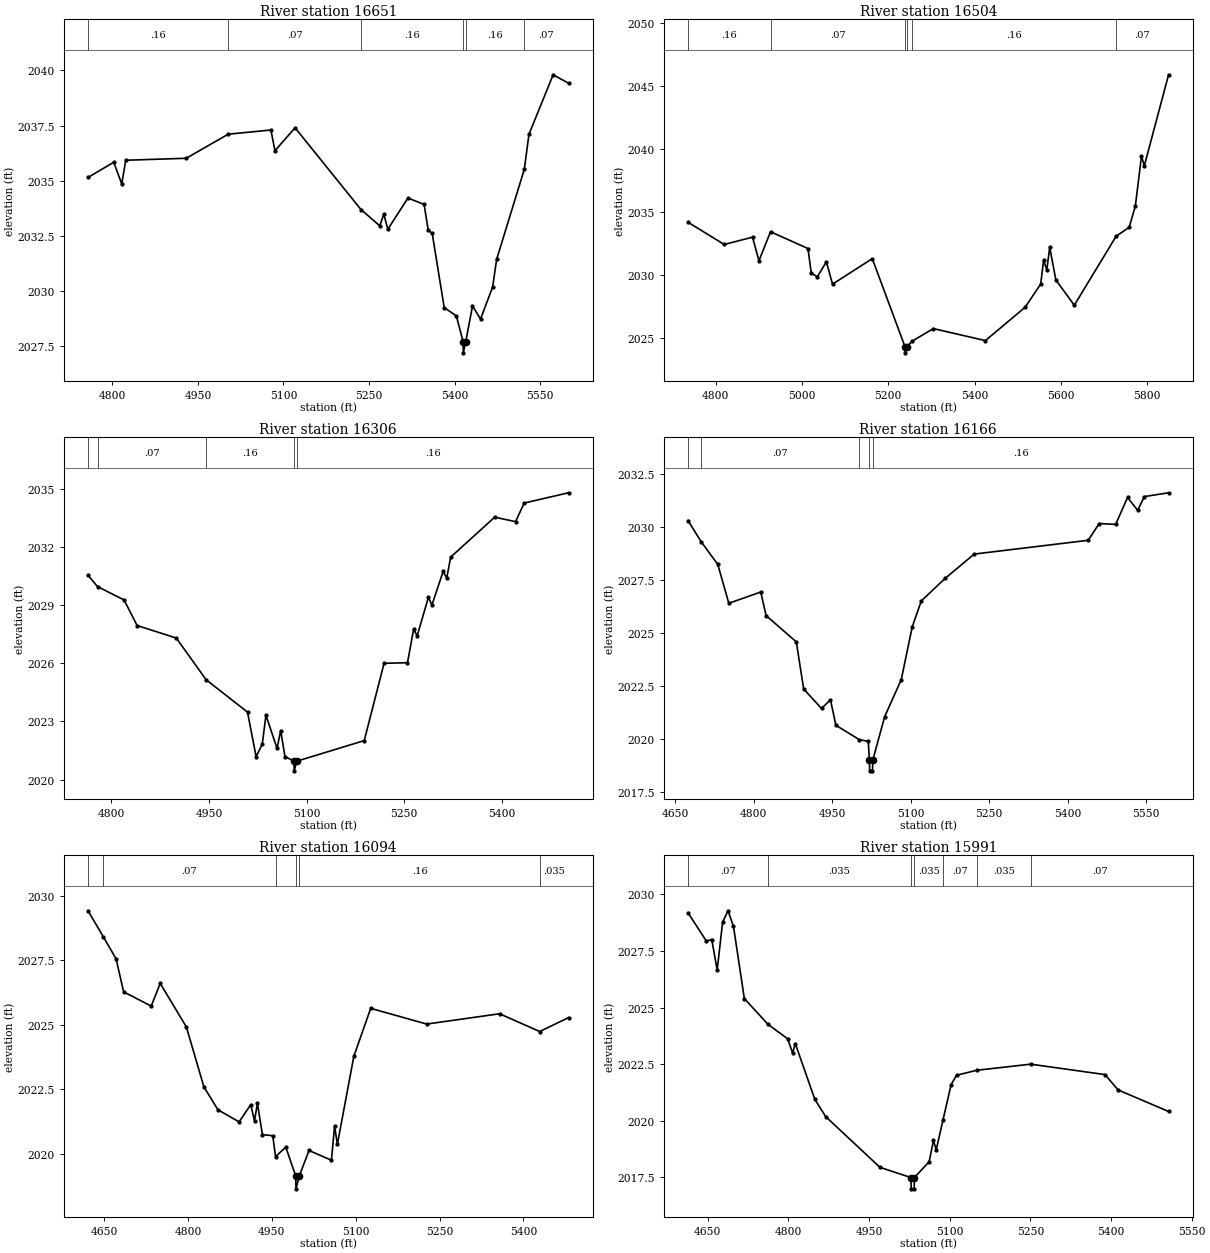
Type RM Length L Ch R = 1 ,16651   ,147,147,147
BEGIN DESCRIPTION:
Elm 01 22 16650.92
END DESCRIPTION:
XS GIS Cut Line= 2
      1525299.34      6802176.03      1525900.47      6801585.31
#Sta/Elev= 30
  4757.1 2035.15  4802.2 2035.84  4816.3 2034.86  4823.3 2035.93  4929.5 2036.02
    5003 2037.11  5077.9  2037.3    5085 2036.36  5120.3  2037.4  5235.8  2033.7
  5268.9 2032.96  5275.9 2033.49    5283 2032.81  5318.3 2034.22  5346.6 2033.93
  5353.8 2032.77  5360.8 2032.62  5381.9 2029.26  5403.2 2028.88  5415.1 2027.71
  5415.4 2027.21  5419.6 2027.71  5431.5 2029.33  5445.6 2028.74  5466.8 2030.19
  5473.9 2031.45  5522.4 2035.52  5530.5  2037.1  5572.9  2039.8  5599.9 2039.42
#Mann= 6 ,-1 , 0
  4757.1     .16       0    5003     .07       0  5235.8     .16       0
  5415.1     .07       0  5419.6     .16       0  5522.4     .07       0
Bank Sta=5415.1,5419.6
XS Rating Curve= 0 ,0
Exp/Cntr=0.3,0.1

Type RM Length L Ch R = 1 ,16504   ,198,198,198
BEGIN DESCRIPTION:
Elm 01 22 16503.76
END DESCRIPTION:
XS GIS Cut Line= 3
       1525359.3      6802259.31      1525575.41       6802110.9
      1526217.48      6801552.01
#Sta/Elev= 30
  4736.1 2034.18  4819.9 2032.42  4885.5    2033  4900.4 2031.13  4927.2 2033.43
    5014  2032.1  5021.6 2030.15  5035.8 2029.87  5056.7 2031.05  5070.9 2029.28
    5163  2031.3  5238.6 2024.34  5238.9 2023.84  5243.1 2024.34  5256.1 2024.78
  5304.5 2025.76  5425.1 2024.81  5517.2 2027.45  5553.3 2029.29  5559.9 2031.16
  5567.5 2030.43  5574.1 2032.19  5588.4 2029.61  5631.1 2027.61  5728.2 2033.08
  5758.3 2033.78  5772.6 2035.48  5786.8 2039.42  5793.4 2038.65  5849.5 2045.86
#Mann= 6 ,-1 , 0
  4736.1     .16       0  4927.2     .07       0  5238.6     .07       0
  5243.1     .07       0  5256.1     .16       0  5728.2     .07       0
Bank Sta=5238.6,5243.1
XS Rating Curve= 0 ,0
Exp/Cntr=0.3,0.1

Type RM Length L Ch R = 1 ,16306   ,140,140,140
BEGIN DESCRIPTION:
Elm 01 22 16305.685
END DESCRIPTION:
XS GIS Cut Line= 3
      1525499.84      6802241.11      1525734.84      6802218.39
      1526188.48      6802002.24
#Sta/Elev= 30
  4763.9 2030.54  4778.5 2029.96  4819.3 2029.27  4839.4 2027.95  4899.7  2027.3
  4945.5 2025.15  5009.1 2023.48  5022.3 2021.18  5031.8 2021.83  5037.4 2023.32
  5054.5 2021.61  5060.1 2022.53  5066.6 2021.19  5080.5 2020.95  5080.8 2020.45
    5085 2020.95  5188.5 2022.01    5219    2026    5255 2026.03  5264.4 2027.75
  5269.9 2027.42  5287.1  2029.4  5292.6 2029.01  5309.8 2030.74  5315.3  2030.4
  5321.4 2031.48    5389 2033.54  5421.1 2033.31  5434.4 2034.27  5502.5  2034.8
#Mann= 5 ,-1 , 0
  4763.9     .16       0  4778.5     .07       0  4945.5     .16       0
  5080.5     .07       0    5085     .16       0
Bank Sta=5080.5,5085
XS Rating Curve= 0 ,0
Exp/Cntr=0.3,0.1

Type RM Length L Ch R = 1 ,16166   ,72,72,72
BEGIN DESCRIPTION:
Elm 01 22 16165.65
END DESCRIPTION:
XS GIS Cut Line= 3
      1525489.48      6802256.74      1525809.78      6802329.65
      1526371.15      6802147.73
#Sta/Elev= 30
  4674.4 2030.31  4699.2 2029.32  4731.3 2028.24  4752.3 2026.41  4813.4 2026.94
  4823.6 2025.83  4881.4 2024.59  4895.4 2022.37  4929.6 2021.45  4946.7 2021.86
    4957 2020.66  5001.8 2019.98  5018.9  2019.9  5021.1 2019.01  5021.6 2018.51
    5027 2018.51  5027.5 2019.01  5050.4 2021.07    5082 2022.81    5103  2025.3
  5120.3 2026.52  5166.1 2027.59  5221.5 2028.73  5439.4 2029.38  5460.4 2030.17
  5491.9 2030.13  5514.6  2031.4    5534 2030.79  5546.6 2031.44    5593 2031.62
#Mann= 5 ,-1 , 0
  4674.4     .16       0  4699.2     .07       0  5001.8     .16       0
  5021.1     .07       0  5027.5     .16       0
Bank Sta=5021.1,5027.5
XS Rating Curve= 0 ,0
Exp/Cntr=0.3,0.1

Type RM Length L Ch R = 1 ,16094   ,103,103,103
BEGIN DESCRIPTION:
Elm 01 22 16093.63
END DESCRIPTION:
XS GIS Cut Line= 3
       1525486.9      6802274.97      1525859.26      6802389.55
      1526328.03       6802420.8
#Sta/Elev= 30
  4621.2 2029.43  4648.6 2028.42  4671.5 2027.56  4684.9 2026.28  4734.3 2025.73
  4750.3 2026.61  4797.1 2024.92  4828.5 2022.59  4853.6  2021.7  4891.5 2021.23
  4912.2  2021.9    4919 2021.27  4924.2 2021.95  4933.1 2020.74  4951.7 2020.69
  4956.6 2019.88  4974.9 2020.25  4992.7 2019.13  4993.2 2018.63  4999.1 2019.13
  5016.5 2020.12  5056.6 2019.74  5062.2 2021.07  5067.2 2020.36  5096.7 2023.78
  5126.8 2025.64    5227 2025.03  5357.3 2025.43  5429.1 2024.74  5480.6 2025.28
#Mann= 6 ,-1 , 0
  4621.2     .16       0  4648.6     .07       0  4956.6     .16       0
  4992.7     .07       0  4999.1     .16       0  5429.1    .035       0
Bank Sta=4992.7,4999.1
XS Rating Curve= 0 ,0
Exp/Cntr=0.3,0.1

Type RM Length L Ch R = 1 ,15991   ,123,123,123
BEGIN DESCRIPTION:
Elm 01 22 15990.82
END DESCRIPTION:
XS GIS Cut Line= 3
      1525471.25      6802436.42      1525856.66       6802488.5
      1526350.72      6802592.52
#Sta/Elev= 30
  4613.2 2029.19  4647.3 2027.94  4657.3 2028.01  4667.4 2026.66  4677.5 2028.78
  4687.6 2029.28  4697.7 2028.59  4717.9  2025.4    4762 2024.26  4798.6 2023.62
  4807.7 2022.99  4812.7 2023.41  4849.1 2020.94  4869.3 2020.18  4970.2 2017.94
  5027.8 2017.49  5028.3 2016.99  5033.8 2016.99  5034.3 2017.49  5061.7 2018.19
  5069.7 2019.13  5074.8 2018.71  5087.6 2020.05  5102.6  2021.6  5112.8 2022.01
    5150 2022.23  5250.5  2022.5  5388.7 2022.04  5413.3 2021.36    5507 2020.41
#Mann= 7 ,-1 , 0
  4613.2     .07       0    4762    .035       0  5027.8    .035       0
  5034.3    .035       0  5087.6     .07       0    5150    .035       0
  5250.5     .07       0
Bank Sta=5027.8,5034.3
XS Rating Curve= 0 ,0
Exp/Cntr=0.3,0.1