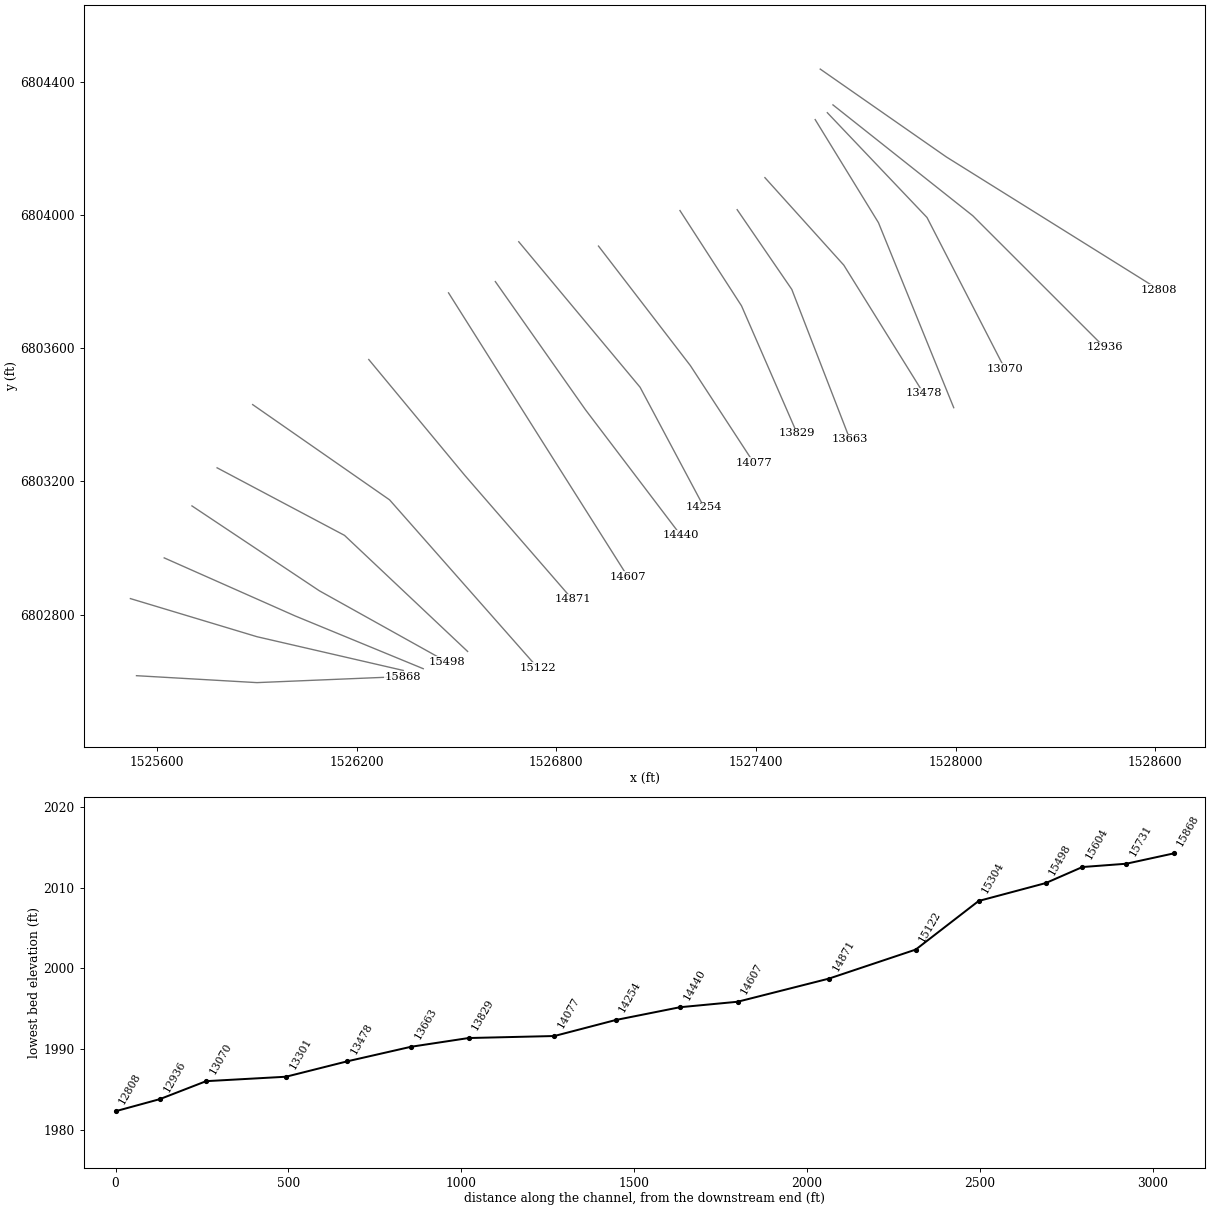
HEC-RAS study Elm 01 22.prj: Elm 01 22 Base Level Engineering

--- Elm 01 22.g01 (geometry) --- (continued)

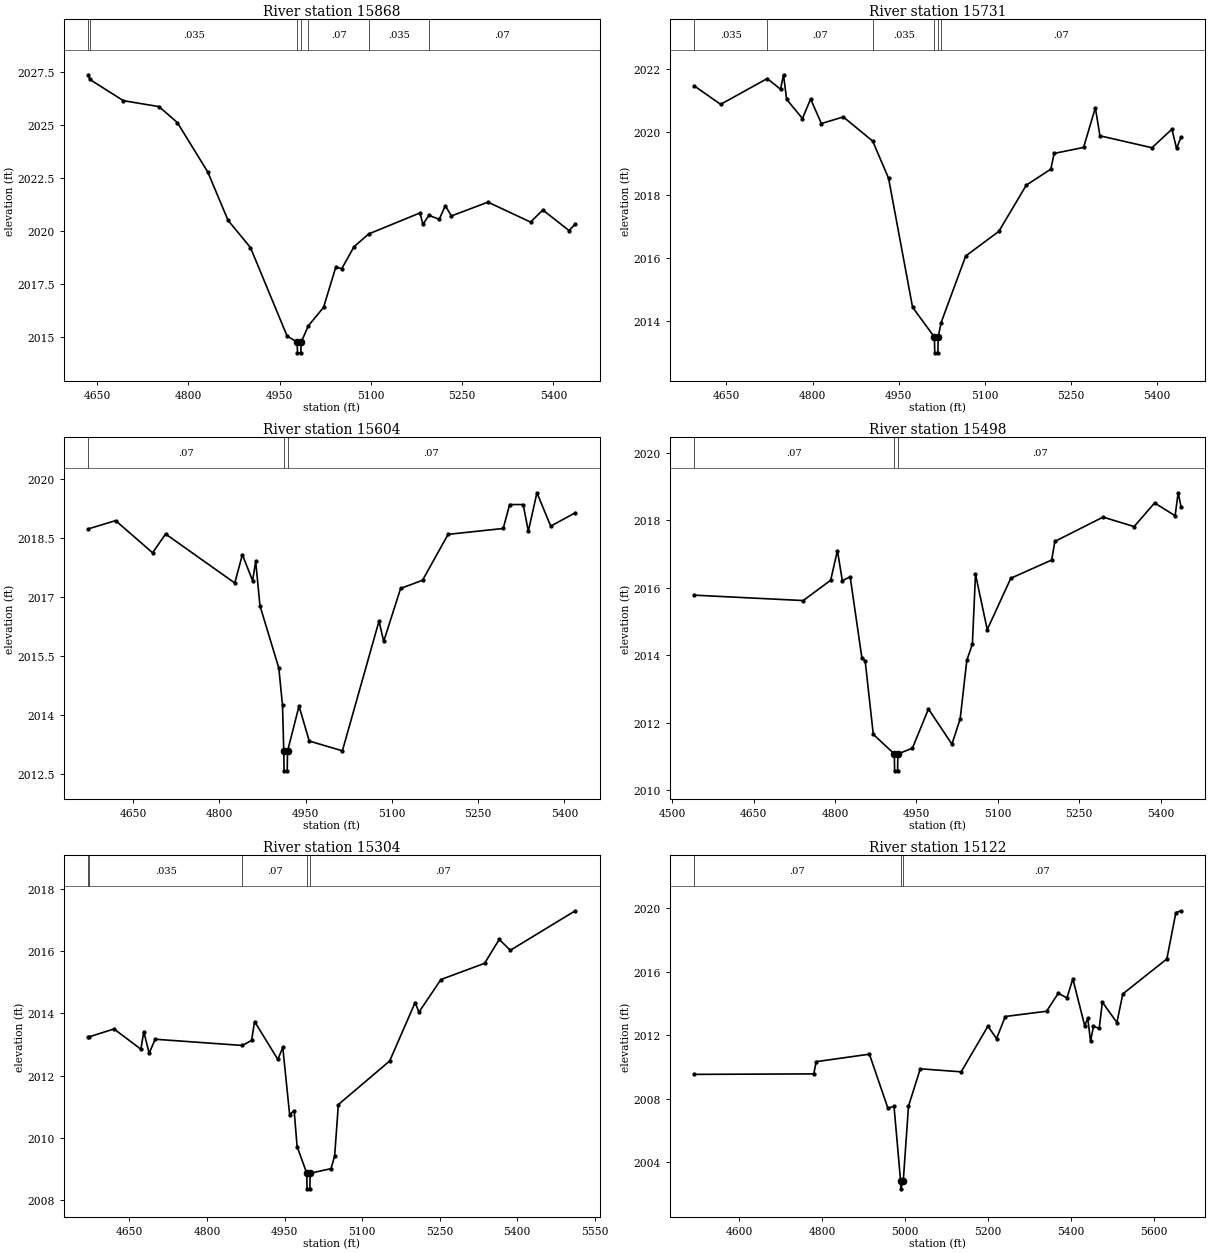
Type RM Length L Ch R = 1 ,15868   ,137,137,137
BEGIN DESCRIPTION:
Elm 01 22 15868.02
END DESCRIPTION:
XS GIS Cut Line= 3
      1525538.98      6802616.11      1525900.93      6802595.27
       1526338.4       6802613.5
#Sta/Elev= 30
  4635.5 2027.36    4638 2027.14  4693.1 2026.14  4751.7 2025.86  4781.8 2025.11
  4831.8 2022.78  4865.2  2020.5    4902 2019.22  4962.1 2015.06  4978.8 2014.76
  4979.3 2014.26  4984.8 2014.26  4985.3 2014.76  4997.3 2015.54  5022.1  2016.4
  5042.2 2018.29  5052.2 2018.23  5072.2 2019.26  5096.3 2019.86  5180.5 2020.85
  5185.5 2020.31  5195.2 2020.74  5212.3 2020.55  5222.3 2021.19  5232.3 2020.71
  5292.4 2021.36  5362.4 2020.42  5382.5 2020.99  5425.7 2020.02  5435.9 2020.33
#Mann= 7 ,-1 , 0
  4635.5     .07       0    4638    .035       0  4978.8     .07       0
  4985.3    .035       0  4997.3     .07       0  5096.3    .035       0
  5195.2     .07       0
Bank Sta=4978.8,4985.3
XS Rating Curve= 0 ,0
Exp/Cntr=0.3,0.1

Type RM Length L Ch R = 1 ,15731   ,127,127,127
BEGIN DESCRIPTION:
Elm 01 22 15730.84
END DESCRIPTION:
XS GIS Cut Line= 3
      1525520.72      6802847.88      1525900.93       6802733.3
      1526340.48      6802631.86
#Sta/Elev= 30
  4593.7 2021.47  4639.9 2020.88  4721.1  2021.7  4744.2 2021.36  4749.4 2021.82
  4754.8 2021.04  4782.4 2020.43  4796.6 2021.05  4815.4 2020.27  4853.6 2020.48
  4904.8 2019.71  4932.4 2018.53  4974.2 2014.43  5012.3 2013.48  5012.8 2012.98
  5018.3 2012.98  5018.8 2013.48  5023.9 2013.94  5066.8 2016.06  5124.4 2016.84
  5172.3 2018.31    5215 2018.82  5220.8 2019.32  5272.1 2019.51  5292.6 2020.77
  5300.6 2019.88  5391.2  2019.5    5426 2020.09    5434 2019.48  5441.9 2019.84
#Mann= 6 ,-1 , 0
  4593.7    .035       0  4721.1     .07       0  4904.8    .035       0
  5012.3    .035       0  5018.8    .035       0  5023.9     .07       0
Bank Sta=5012.3,5018.8
XS Rating Curve= 0 ,0
Exp/Cntr=0.3,0.1

Type RM Length L Ch R = 1 ,15604   ,106,106,106
BEGIN DESCRIPTION:
Elm 01 22 15604.05
END DESCRIPTION:
XS GIS Cut Line= 3
      1525622.26      6802970.28      1526015.51       6802795.8
      1526400.47      6802637.13
#Sta/Elev= 30
  4572.3 2018.74  4619.7 2018.95  4684.1 2018.13  4706.6 2018.61  4826.9 2017.36
  4840.1 2018.08  4857.9 2017.42  4863.3 2017.91  4870.7 2016.78  4903.5 2015.19
  4909.9 2014.24  4912.1 2013.07  4912.6 2012.57  4918.1 2012.57  4918.6 2013.07
  4938.6 2014.22  4956.4 2013.33    5014 2013.08  5077.7 2016.39  5085.8 2015.87
  5115.2 2017.22  5153.4 2017.43  5197.8  2018.6  5293.6 2018.75  5304.8 2019.36
  5328.3 2019.36  5337.3 2018.68  5352.2 2019.66  5376.2 2018.81  5418.9 2019.15
#Mann= 3 ,-1 , 0
  4572.3     .07       0  4912.1     .07       0  4918.6     .07       0
Bank Sta=4912.1,4918.6
XS Rating Curve= 0 ,0
Exp/Cntr=0.3,0.1

Type RM Length L Ch R = 1 ,15498   ,194,194,194
BEGIN DESCRIPTION:
Elm 01 22 15498.24
END DESCRIPTION:
XS GIS Cut Line= 3
       1525705.6      6803126.54      1526088.43      6802871.32
      1526470.58      6802658.14
#Sta/Elev= 30
  4540.2 2015.78  4741.3 2015.62  4791.9 2016.22  4804.4  2017.1  4813.4 2016.21
  4827.9 2016.32  4849.5 2013.92  4855.5 2013.84  4870.5 2011.66  4909.3 2011.08
  4909.8 2010.58  4915.3 2010.58  4915.8 2011.08  4942.6 2011.25  4972.2 2012.41
  5015.5 2011.37  5030.7 2012.12  5042.9 2013.85  5053.2 2014.33  5058.9  2016.4
  5080.6 2014.76    5124 2016.28  5199.4 2016.82  5205.2 2017.37  5294.1 2018.09
  5351.4 2017.81  5389.1 2018.51  5426.9 2018.13  5432.6 2018.81  5437.9 2018.39
#Mann= 3 ,-1 , 0
  4540.2     .07       0  4909.3     .07       0  4915.8     .07       0
Bank Sta=4909.3,4915.8
XS Rating Curve= 0 ,0
Exp/Cntr=0.3,0.1

Type RM Length L Ch R = 1 ,15304   ,182,182,182
BEGIN DESCRIPTION:
Elm 01 22 15303.55
END DESCRIPTION:
XS GIS Cut Line= 3
      1525781.13      6803241.11      1526163.95      6803037.98
      1526533.73      6802689.03
#Sta/Elev= 30
  4570.5 2013.25  4572.6 2013.25  4620.2  2013.5  4672.1 2012.85  4677.8 2013.41
  4688.1 2012.72  4699.8 2013.17  4868.2 2012.97  4886.3 2013.13    4892 2013.74
  4937.1 2012.52  4946.6 2012.91  4959.8 2010.75  4968.6 2010.87  4974.3 2009.72
    4993 2008.86  4993.5 2008.36    4999 2008.36  4999.5 2008.86    5040 2009.01
  5046.9 2009.42  5054.1 2011.07  5153.3 2012.47  5202.6 2014.35  5209.9 2014.04
  5252.4 2015.09  5336.9 2015.61  5365.2 2016.38  5386.7 2016.03  5512.3  2017.3
#Mann= 5 ,-1 , 0
  4570.5     .07       0  4572.6    .035       0  4868.2     .07       0
    4993     .07       0  4999.5     .07       0
Bank Sta=4993,4999.5
XS Rating Curve= 0 ,0
Exp/Cntr=0.3,0.1

Type RM Length L Ch R = 1 ,15122   ,251,251,251
BEGIN DESCRIPTION:
Elm 01 22 15121.87
END DESCRIPTION:
XS GIS Cut Line= 3
      1525887.95      6803431.18      1526299.36      6803144.75
      1526744.71      6802639.51
#Sta/Elev= 30
  4490.7 2009.53  4779.3 2009.56  4785.3 2010.33  4913.6  2010.8  4958.1 2007.41
    4973 2007.51  4988.8 2002.83  4989.3 2002.33  4995.3 2002.83  5007.9 2007.53
  5036.3 2009.88    5135 2009.69  5199.5 2012.56  5220.4 2011.78  5241.3 2013.17
  5340.9  2013.5  5369.3 2014.63  5390.2 2014.34  5404.4 2015.54  5432.9  2012.6
  5440.4 2013.05  5447.1 2011.62  5454.2 2012.55    5468 2012.42  5475.6 2014.07
  5510.7 2012.79  5524.9 2014.59  5631.2 2016.79    5653 2019.71  5665.5 2019.82
#Mann= 3 ,-1 , 0
  4490.7     .07       0  4988.8     .07       0  4995.3     .07       0
Bank Sta=4988.8,4995.3
XS Rating Curve= 0 ,0
Exp/Cntr=0.3,0.1

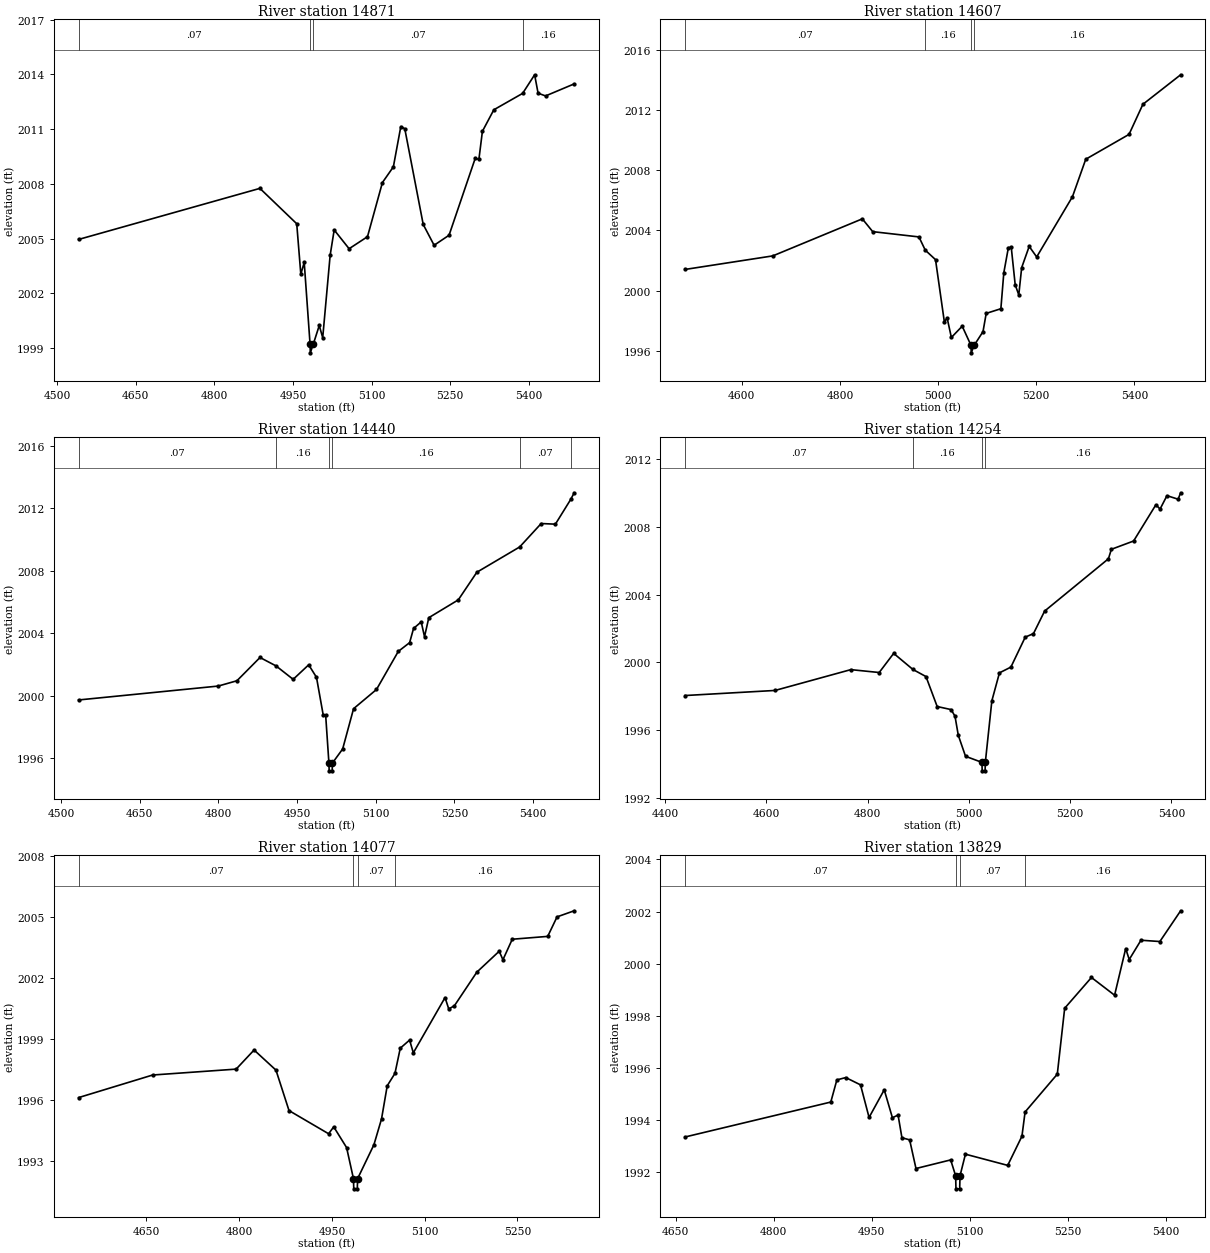
Type RM Length L Ch R = 1 ,14871   ,264,264,264
BEGIN DESCRIPTION:
Elm 01 22 14870.99
END DESCRIPTION:
XS GIS Cut Line= 3
      1526236.84      6803566.66      1526525.93      6803217.67
      1526848.86      6802845.26
#Sta/Elev= 30
  4540.8 2004.95  4886.9 2007.75  4957.2 2005.81    4965 2003.04  4971.5 2003.69
  4982.6 1999.23  4983.1 1998.73  4989.1 1999.23  5000.2 2000.23  5006.8 1999.56
    5021 2004.08  5028.7 2005.47  5057.2 2004.44  5092.3  2005.1  5120.8 2008.07
  5141.7 2008.93  5155.9 2011.14  5163.5 2011.02  5198.7 2005.77  5219.5 2004.63
    5248 2005.18    5298  2009.4    5305 2009.34  5311.7 2010.88  5333.5 2012.06
  5388.5 2012.96  5411.4 2013.98    5418 2012.97  5432.3 2012.82  5486.9 2013.48
#Mann= 4 ,-1 , 0
  4540.8     .07       0  4982.6     .07       0  4989.1     .07       0
  5388.5     .16       0
Bank Sta=4982.6,4989.1
XS Rating Curve= 0 ,0
Exp/Cntr=0.3,0.1

Type RM Length L Ch R = 1 ,14607   ,167,167,167
BEGIN DESCRIPTION:
Elm 01 22 14606.63
END DESCRIPTION:
XS GIS Cut Line= 3
      1526476.47      6803767.11      1526747.28      6803337.46
      1527015.51      6802912.98
#Sta/Elev= 30
  4484.3  2001.4  4663.1  2002.3  4845.5 2004.76  4866.7 2003.91  4960.9 2003.56
  4973.8 2002.68  4994.7 2002.05  5012.6 1997.94  5018.5 1998.16    5027 1996.88
  5049.1 1997.63    5067 1996.36  5067.5 1995.86  5073.5 1996.36  5091.5 1997.27
    5098 1998.48  5127.9 1998.79  5133.9 2001.18  5143.2 2002.85  5149.1 2002.86
  5157.1 2000.38  5164.4 1999.71  5170.3 2001.52  5185.6 2002.93  5200.9 2002.23
  5273.8 2006.23  5300.9 2008.72  5389.1 2010.37  5417.4 2012.37  5494.3 2014.33
#Mann= 4 ,-1 , 0
  4484.3     .07       0  4973.8     .16       0    5067     .07       0
  5073.5     .16       0
Bank Sta=5067,5073.5
XS Rating Curve= 0 ,0
Exp/Cntr=0.3,0.1

Type RM Length L Ch R = 1 ,14440   ,186,186,186
BEGIN DESCRIPTION:
Elm 01 22 14440.27
END DESCRIPTION:
XS GIS Cut Line= 3
      1526617.07      6803801.01      1526887.91      6803415.59
      1527174.35      6803038.01
#Sta/Elev= 30
  4533.3 1999.72  4799.5 2000.61  4835.2 2000.95  4879.2 2002.44  4909.8  2001.9
  4942.4 2001.04    4972 2001.97  4986.9 2001.17  4999.8 1998.74  5004.4 1998.74
  5010.6 1995.68  5011.1 1995.18  5016.8 1995.18  5017.3 1995.68  5036.8 1996.58
  5057.6 1999.16  5101.3 2000.39  5142.9 2002.83  5164.5 2003.39    5172  2004.3
  5186.6 2004.72  5192.9 2003.77  5201.1 2004.99  5257.3 2006.13  5292.7  2007.9
  5374.4 2009.52  5415.4 2011.02  5442.5 2010.98  5471.8 2012.57  5478.3 2012.99
#Mann= 6 ,-1 , 0
  4533.3     .07       0  4909.8     .16       0  5010.6     .07       0
  5017.3     .16       0  5374.4     .07       0  5471.8     .16       0
Bank Sta=5010.6,5017.3
XS Rating Curve= 0 ,0
Exp/Cntr=0.3,0.1

Type RM Length L Ch R = 1 ,14254   ,177,177,177
BEGIN DESCRIPTION:
Elm 01 22 14253.53
END DESCRIPTION:
XS GIS Cut Line= 3
      1526687.41      6803920.77      1527051.97       6803483.3
      1527244.23      6803122.15
#Sta/Elev= 30
  4439.6 1998.04  4617.2 1998.34  4766.9 1999.57  4822.9  1999.4  4851.5 2000.53
  4889.5 1999.58  4915.3 1999.16  4937.4 1997.39  4964.8 1997.21  4972.6 1996.82
  4979.1 1995.69  4993.4 1994.45  5025.8 1994.09  5026.3 1993.59    5032 1993.59
  5032.5 1994.09  5045.4 1997.73  5060.4 1999.38    5083 1999.72  5111.3 2001.49
  5127.6  2001.7  5149.6 2003.03  5275.6 2006.12  5281.4 2006.68  5325.3 2007.17
  5369.3 2009.31  5377.6 2009.06  5391.2 2009.85  5413.2 2009.64  5418.2 2010.02
#Mann= 4 ,-1 , 0
  4439.6     .07       0  4889.5     .16       0  5025.8     .07       0
  5032.5     .16       0
Bank Sta=5025.8,5032.5
XS Rating Curve= 0 ,0
Exp/Cntr=0.3,0.1

Type RM Length L Ch R = 1 ,14077   ,248,248,248
BEGIN DESCRIPTION:
Elm 01 22 14077.15
END DESCRIPTION:
XS GIS Cut Line= 3
      1526926.97      6803907.78      1527203.01       6803548.4
      1527393.11      6803256.74
#Sta/Elev= 30
  4540.5  1996.1  4660.2 1997.21  4795.2  1997.5  4824.2 1998.44  4859.6 1997.45
  4880.7 1995.46  4944.7 1994.32    4953 1994.66  4973.8 1993.64  4984.9 1992.11
  4985.4 1991.61  4991.1 1991.61  4991.6 1992.11    5018 1993.78  5030.3 1995.05
  5039.5 1996.68    5052 1997.29  5060.6 1998.53  5075.7 1998.93  5081.7  1998.3
    5133 2001.02    5139 2000.46  5148.2 2000.62  5184.4 2002.27  5220.6  2003.3
  5226.6 2002.88  5241.7 2003.89    5299 2004.03  5314.1 2004.99  5341.8 2005.29
#Mann= 4 ,-1 , 0
  4540.5     .07       0  4984.9     .07       0  4991.6     .07       0
    5052     .16       0
Bank Sta=4984.9,4991.6
XS Rating Curve= 0 ,0
Exp/Cntr=0.3,0.1

Type RM Length L Ch R = 1 ,13829   ,166,166,166
BEGIN DESCRIPTION:
Elm 01 22 13828.94
END DESCRIPTION:
XS GIS Cut Line= 3
      1527171.75      6804014.57      1527356.66      6803728.09
      1527523.33      6803345.27
#Sta/Elev= 30
  4664.5 1993.35  4887.5 1994.69  4896.8 1995.54  4910.4 1995.63    4933 1995.35
  4946.1  1994.1  4969.3 1995.16  4981.8 1994.09  4990.5 1994.19  4996.4 1993.32
  5008.2 1993.24  5017.9 1992.14    5071 1992.47  5078.6 1991.86  5079.1 1991.36
  5084.8 1991.36  5085.3 1991.86  5093.6 1992.69  5158.3 1992.26  5180.1 1993.38
  5184.9 1994.31  5234.2 1995.76  5245.5 1998.29  5286.5 1999.47  5321.9 1998.79
  5338.9 2000.58  5344.3 2000.16  5362.3  2000.9  5391.2 2000.85    5423 2002.03
#Mann= 4 ,-1 , 0
  4664.5     .07       0  5078.6     .07       0  5085.3     .07       0
  5184.9     .16       0
Bank Sta=5078.6,5085.3
XS Rating Curve= 0 ,0
Exp/Cntr=0.3,0.1

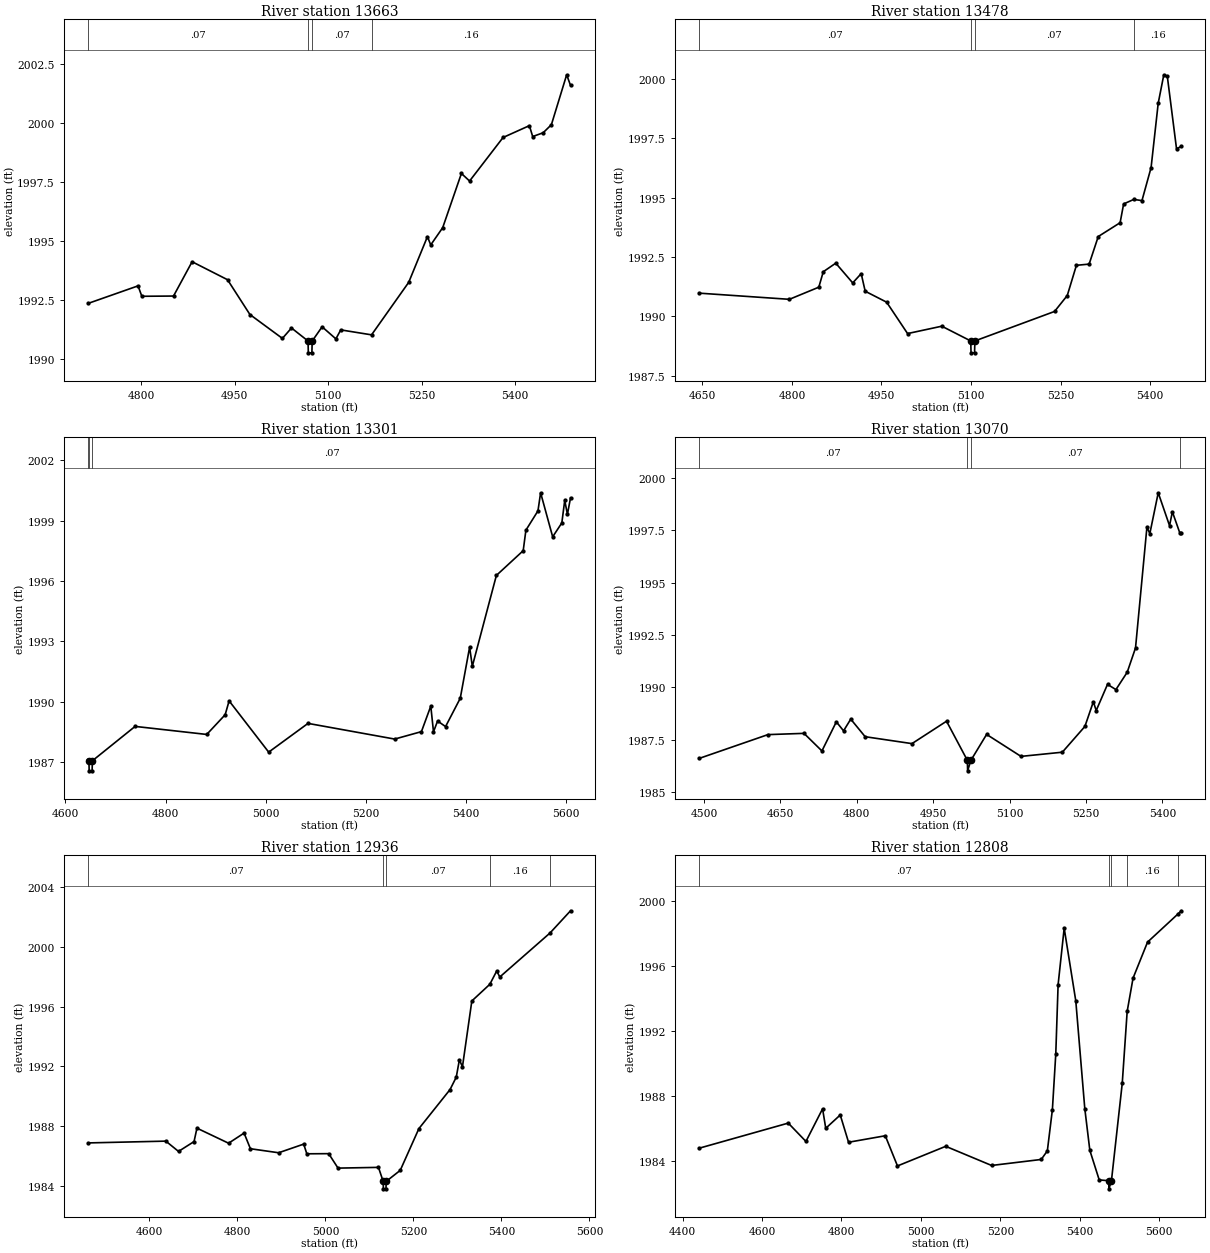
Type RM Length L Ch R = 1 ,13663   ,185,185,185
BEGIN DESCRIPTION:
Elm 01 22 13662.78
END DESCRIPTION:
XS GIS Cut Line= 3
      1527343.62      6804017.17       1527507.7      6803777.57
      1527682.17      6803327.07
#Sta/Elev= 30
  4715.2 1992.37  4795.1 1993.11  4801.2 1992.67    4852 1992.68  4881.8 1994.13
  4938.6 1993.37  4974.5  1991.9  5026.6 1990.89  5041.2 1991.33  5067.7 1990.78
  5068.2 1990.28  5073.9 1990.28  5074.4 1990.78  5090.3 1991.38  5112.4 1990.87
  5120.2 1991.25  5169.6 1991.04  5229.2 1993.26  5259.2 1995.19  5264.5 1994.84
  5283.7 1995.57  5313.7 1997.86  5326.8 1997.54  5380.5 1999.38  5422.7 1999.88
    5428 1999.42  5444.8 1999.58    5458 1999.92  5482.5 2002.03  5488.7 2001.58
#Mann= 4 ,-1 , 0
  4715.2     .07       0  5067.7     .07       0  5074.4     .07       0
  5169.6     .16       0
Bank Sta=5067.7,5074.4
XS Rating Curve= 0 ,0
Exp/Cntr=0.3,0.1

Type RM Length L Ch R = 1 ,13478   ,177,177,177
BEGIN DESCRIPTION:
Elm 01 22 13478.42
END DESCRIPTION:
XS GIS Cut Line= 3
      1527426.94      6804113.53      1527663.95      6803850.48
      1527903.54      6803465.06
#Sta/Elev= 30
  4644.3 1990.98  4795.7 1990.72    4845 1991.23  4852.5 1991.88  4873.4 1992.24
  4901.8 1991.41    4916  1991.8  4922.7 1991.06  4958.6  1990.6  4993.7 1989.28
    5051 1989.59  5099.5 1988.97    5100 1988.47  5105.9 1988.47  5106.4 1988.97
  5239.9 1990.21  5261.2 1990.88  5276.5 1992.15  5297.8  1992.2  5313.1 1993.36
  5349.7 1993.94  5355.6 1994.73  5372.6 1994.92  5386.3 1994.87  5401.6 1996.26
  5413.5 1998.96  5422.9 2000.16  5428.8 2000.09  5444.2 1997.05  5452.2 1997.15
#Mann= 4 ,-1 , 0
  4644.3     .07       0  5099.5     .07       0  5106.4     .07       0
  5372.6     .16       0
Bank Sta=5099.5,5106.4
XS Rating Curve= 0 ,0
Exp/Cntr=0.3,0.1

Type RM Length L Ch R = 1 ,13301   ,231,231,231
BEGIN DESCRIPTION:
Elm 01 22 13300.83
END DESCRIPTION:
XS GIS Cut Line= 3
      1527577.99      6804288.02      1527768.11      6803978.09
      1527994.23       6803421.9
#Sta/Elev= 30
  4645.5 1987.11  4646.9 1987.06  4647.4 1986.56  4653.3 1986.56  4653.8 1987.06
  4739.2 1988.77  4882.4 1988.37  4919.2 1989.35  4927.1 1990.04  5006.2 1987.49
  5084.8 1988.92    5258 1988.14  5311.5 1988.51  5330.2 1989.78  5335.6  1988.5
  5343.8 1989.04  5359.7 1988.76  5389.1 1990.17  5407.8 1992.71  5413.2 1991.76
  5461.3 1996.28  5514.9 1997.51  5520.3 1998.53  5544.4 1999.49  5549.7 2000.39
  5573.8  1998.2  5592.1 1998.89  5597.9 2000.01  5603.3 1999.32  5609.5 2000.14
#Mann= 3 ,-1 , 0
  4645.5     .07       0  4646.9     .07       0  4653.8     .07       0
Bank Sta=4646.9,4653.8
XS Rating Curve= 0 ,0
Exp/Cntr=0.3,0.1

Type RM Length L Ch R = 1 ,13070   ,134,134,134
BEGIN DESCRIPTION:
Elm 01 22 13070.25
END DESCRIPTION:
XS GIS Cut Line= 3
      1527614.49      6804308.79      1527913.95      6803993.71
       1528148.3      6803538.03
#Sta/Elev= 30
    4490  1986.6  4625.4 1987.74  4696.2  1987.8  4731.4 1986.96  4759.7 1988.35
  4773.9 1987.92    4788 1988.48  4816.3 1987.64  4908.2 1987.31  4976.1 1988.38
    5017 1986.51  5017.5 1986.01  5023.9 1986.51  5054.8 1987.75  5122.3  1986.7
  5203.5  1986.9  5247.8 1988.13  5264.4 1989.31    5270 1988.89  5292.2 1990.14
  5308.7 1989.89  5330.9 1990.72  5347.2 1991.88  5369.6 1997.65  5375.3 1997.34
  5391.8 1999.29    5414 1997.72  5419.6 1998.38  5434.5 1997.35  5437.1 1997.35
#Mann= 4 ,-1 , 0
    4490     .07       0    5017     .07       0  5023.9     .07       0
  5434.5     .16       0
Bank Sta=5017,5023.9
XS Rating Curve= 0 ,0
Exp/Cntr=0.3,0.1

Type RM Length L Ch R = 1 ,12936   ,128,128,128
BEGIN DESCRIPTION:
Elm 01 22 12936.04
END DESCRIPTION:
XS GIS Cut Line= 3
      1527631.39      6804332.26      1528051.53      6803998.92
      1528447.36      6803603.09
#Sta/Elev= 30
  4460.8 1986.86  4637.2 1986.98    4666 1986.29  4701.3 1986.95  4707.9 1987.85
  4779.8 1986.84    4815 1987.52  4829.4 1986.47  4893.5  1986.2  4950.5 1986.78
  4957.6 1986.13  5007.3 1986.14  5028.5 1985.17  5120.4 1985.22  5131.1 1984.28
  5131.6 1983.78  5137.5 1983.78    5138 1984.28  5169.9 1985.02  5212.3 1987.82
  5283.1 1990.44  5297.2 1991.27  5304.3 1992.43  5311.3 1991.97  5332.6 1996.38
  5373.5  1997.5  5389.1 1998.39  5396.2 1997.99  5510.3 2000.94  5556.9 2002.43
#Mann= 5 ,-1 , 0
  4460.8     .07       0  5131.1     .07       0    5138     .07       0
  5373.5     .16       0  5510.3     .07       0
Bank Sta=5131.1,5138
XS Rating Curve= 0 ,0
Exp/Cntr=0.3,0.1

Type RM Length L Ch R = 1 ,12808   ,230,230,230
BEGIN DESCRIPTION:
Elm 01 22 12808.47
END DESCRIPTION:
XS GIS Cut Line= 3
      1527593.19       6804439.9      1527971.67        6804176.
       1528610.3      6803776.86
#Sta/Elev= 30
  4441.2 1984.78    4666 1986.33  4710.5  1985.2  4752.4 1987.21  4760.4 1986.01
  4796.9 1986.83  4817.8 1985.15  4910.3 1985.55    4941 1983.69  5062.5  1984.9
    5178 1983.72    5303 1984.09  5318.4 1984.62  5331.1 1987.16  5339.6 1990.58
  5345.5 1994.86  5360.8 1998.34    5390 1993.86  5412.7 1987.22  5425.4 1984.65
    5449 1982.83  5472.9 1982.78  5473.4 1982.28  5479.8 1982.78    5507 1988.78
  5519.4 1993.21  5534.2 1995.26  5570.7 1997.48  5646.3 1999.19  5655.7 1999.41
#Mann= 5 ,-1 , 0
  4441.2     .07       0  5472.9     .07       0  5479.8     .07       0
  5519.4     .16       0  5646.3     .07       0
Bank Sta=5472.9,5479.8
XS Rating Curve= 0 ,0
Exp/Cntr=0.3,0.1