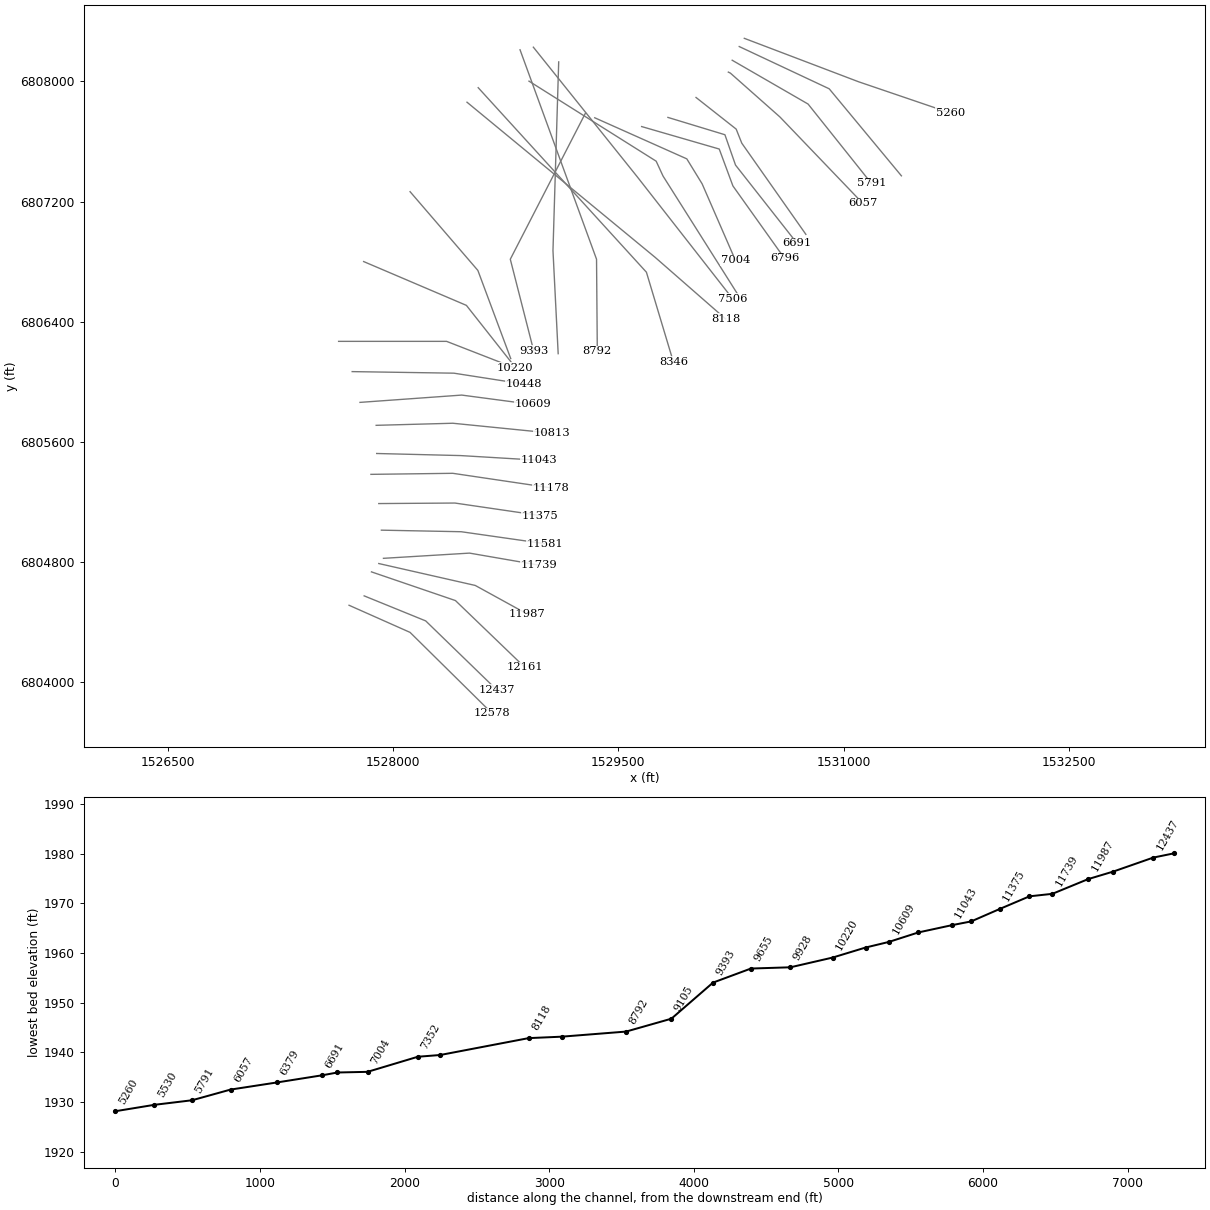
HEC-RAS study Elm 01 22.prj: Elm 01 22 Base Level Engineering

--- Elm 01 22.g01 (geometry) --- (continued)

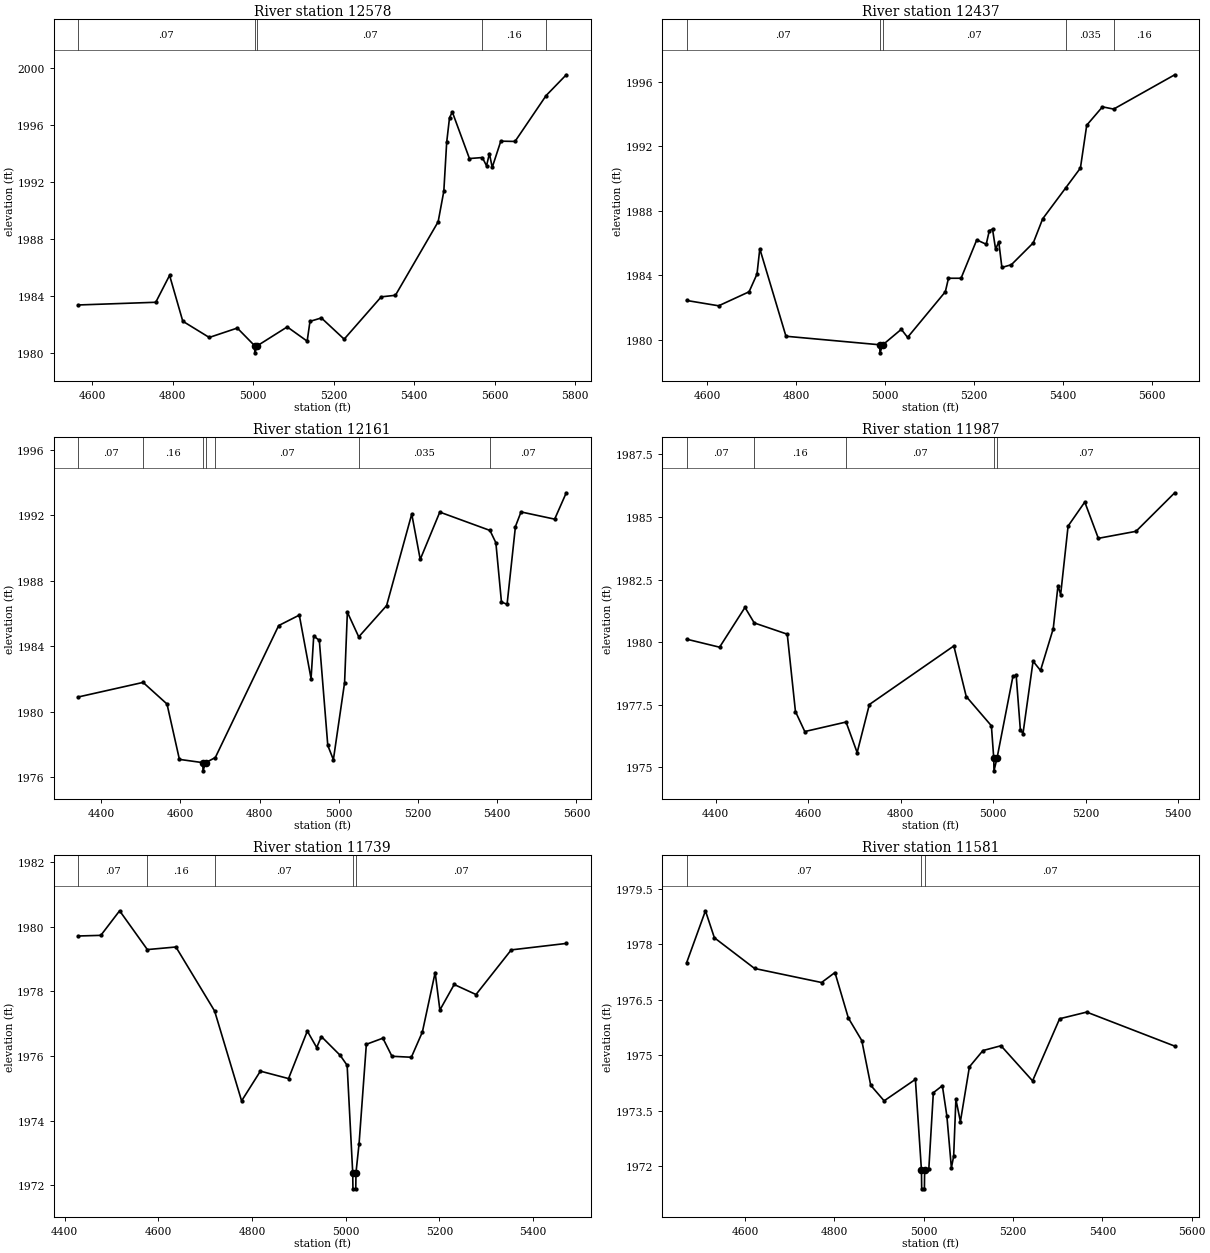
Type RM Length L Ch R = 1 ,12578   ,141,141,141
BEGIN DESCRIPTION:
Elm 01 22 12577.84
END DESCRIPTION:
XS GIS Cut Line= 3
      1527707.76      6804512.82      1528114.03      6804332.25
      1528660.12      6803793.08
#Sta/Elev= 30
  4565.9 1983.39  4758.4 1983.58  4792.7 1985.47  4825.5 1982.25  4891.2 1981.11
  4960.9 1981.77  5003.9 1980.53  5004.4 1980.03  5010.8 1980.53  5084.9 1981.85
  5134.4 1980.85  5141.4 1982.24  5169.7 1982.48  5226.3 1980.99  5318.3 1983.96
  5353.6 1984.07  5459.7 1989.23  5473.8 1991.38  5480.9 1994.81    5488 1996.55
    5495 1996.93  5537.4 1993.67  5569.4 1993.74  5579.9 1993.16    5587 1994.02
    5594 1993.05  5615.3 1994.89  5650.6 1994.87  5727.8 1998.09  5777.9 1999.55
#Mann= 5 ,-1 , 0
  4565.9     .07       0  5003.9     .07       0  5010.8     .07       0
  5569.4     .16       0  5727.8     .07       0
Bank Sta=5003.9,5010.8
XS Rating Curve= 0 ,0
Exp/Cntr=0.3,0.1

Type RM Length L Ch R = 1 ,12437   ,276,276,276
BEGIN DESCRIPTION:
Elm 01 22 12437.21
END DESCRIPTION:
XS GIS Cut Line= 3
      1527808.44      6804575.33       1528218.2      6804408.64
      1528688.81      6803951.87
#Sta/Elev= 30
  4553.3 1982.44  4625.2 1982.11  4693.7 1982.98  4711.5 1984.08  4717.8 1985.65
  4776.7 1980.22  4987.7 1979.69  4988.2 1979.19  4994.7 1979.69  5036.2 1980.65
  5050.4 1980.15  5135.3 1982.98  5142.4 1983.82  5170.7 1983.82    5206  1986.2
  5227.3 1985.93  5234.3 1986.77  5241.5 1986.87  5248.4 1985.63  5255.6 1986.07
  5262.6 1984.49  5283.9 1984.66  5333.3 1986.02  5354.4 1987.51  5406.5 1989.44
  5439.3 1990.66  5453.5 1993.32  5488.9 1994.46  5514.1 1994.32  5651.5 1996.45
#Mann= 5 ,-1 , 0
  4553.3     .07       0  4987.7     .07       0  4994.7     .07       0
  5406.5    .035       0  5514.1     .16       0
Bank Sta=4987.7,4994.7
XS Rating Curve= 0 ,0
Exp/Cntr=0.3,0.1

Type RM Length L Ch R = 1 ,12161   ,174,174,174
BEGIN DESCRIPTION:
Elm 01 22 12161.33
END DESCRIPTION:
XS GIS Cut Line= 3
      1527857.05      6804735.05      1528416.12      6804544.06
       1528877.9      6804099.63
#Sta/Elev= 30
  4342.5 1980.89  4506.1 1981.78  4566.5 1980.46  4597.8 1977.08  4656.9 1976.88
  4657.4 1976.38  4663.9 1976.88  4688.4 1977.19  4848.3 1985.25  4900.4 1985.89
  4930.1 1982.01  4936.8 1984.61  4950.9 1984.35  4972.3 1977.93  4986.4 1977.06
  5014.7 1981.77  5021.7 1986.07  5050.4 1984.56  5120.7 1986.47  5184.2 1992.06
  5205.6 1989.29    5255 1992.18  5381.6 1991.06  5396.5 1990.31  5410.6 1986.69
  5424.8 1986.55  5445.9  1991.3    5460 1992.19  5544.9 1991.75  5574.2 1993.36
#Mann= 7 ,-1 , 0
  4342.5     .07       0  4506.1     .16       0  4656.9     .07       0
  4663.9     .16       0  4688.4     .07       0  5050.4    .035       0
  5381.6     .07       0
Bank Sta=4656.9,4663.9
XS Rating Curve= 0 ,0
Exp/Cntr=0.3,0.1

Type RM Length L Ch R = 1 ,11987   ,248,248,248
BEGIN DESCRIPTION:
Elm 01 22 11986.95
END DESCRIPTION:
XS GIS Cut Line= 3
      1527905.69      6804790.59      1528548.06      6804644.75
      1528895.29      6804453.78
#Sta/Elev= 30
  4337.4 1980.12  4408.5  1979.8  4463.4 1981.39  4483.4 1980.77  4554.8 1980.32
  4572.5 1977.23  4592.7 1976.43  4681.9 1976.81  4705.9 1975.59  4732.3 1977.51
  4914.9 1979.85  4941.7 1977.83  4996.1 1976.66  5001.2 1975.36  5001.7 1974.86
  5008.2 1975.36  5042.6 1978.63  5049.7 1978.67  5058.7  1976.5  5064.4 1976.35
  5086.2 1979.24  5102.3 1978.87  5129.8 1980.54  5140.1 1982.26  5145.8  1981.9
  5161.9 1984.64    5198  1985.6  5227.3 1984.15  5308.7 1984.43  5392.4 1985.97
#Mann= 5 ,-1 , 0
  4337.4     .07       0  4483.4     .16       0  4681.9     .07       0
  5001.2     .07       0  5008.2     .07       0
Bank Sta=5001.2,5008.2
XS Rating Curve= 0 ,0
Exp/Cntr=0.3,0.1

Type RM Length L Ch R = 1 ,11739   ,158,158,158
BEGIN DESCRIPTION:
Elm 01 22 11739.14
END DESCRIPTION:
XS GIS Cut Line= 3
      1527936.91      6804825.31      1528509.87      6804860.03
      1528970.82      6804780.32
#Sta/Elev= 30
  4429.1 1979.71  4477.3 1979.73  4517.4 1980.49  4576.6 1979.29  4637.6 1979.37
  4720.2 1977.39  4777.8 1974.61  4817.9 1975.53    4878  1975.3  4918.1 1976.77
  4938.1 1976.26  4948.1  1976.6  4988.2 1976.02  5003.1 1975.71    5015 1972.39
  5015.5 1971.89  5021.5 1971.89    5022 1972.39  5028.6 1973.29  5044.1 1976.36
  5079.4 1976.55  5098.8 1975.99  5140.2 1975.96  5163.7 1976.74    5191 1978.58
  5201.1 1977.42  5231.6 1978.21  5278.2  1977.9  5353.4 1979.28  5470.9 1979.48
#Mann= 5 ,-1 , 0
  4429.1     .07       0  4576.6     .16       0  4720.2     .07       0
    5015     .07       0    5022     .07       0
Bank Sta=5015,5022
XS Rating Curve= 0 ,0
Exp/Cntr=0.3,0.1

Type RM Length L Ch R = 1 ,11581   ,206,206,206
BEGIN DESCRIPTION:
Elm 01 22 11581.1
END DESCRIPTION:
XS GIS Cut Line= 3
      1527923.02      6805012.81      1528454.31      6805002.39
      1529010.08        6804923.
#Sta/Elev= 30
  4469.3 1977.51  4511.3 1978.91  4531.3 1978.18  4621.3 1977.35  4771.3 1976.97
  4801.3 1977.24  4831.3 1976.01  4861.4  1975.4  4881.4 1974.19  4911.4 1973.77
  4981.4 1974.35    4995 1971.89  4995.5 1971.39  5001.6 1971.39  5002.1 1971.89
  5011.5 1971.93  5021.6 1973.99  5041.8 1974.18  5051.9 1973.36    5062 1971.96
  5067.1 1972.27  5072.1 1973.81  5082.2 1973.21  5102.4 1974.69  5132.7 1975.13
  5173.1 1975.26  5243.8 1974.31  5304.4 1975.99    5365 1976.17  5562.1 1975.25
#Mann= 3 ,-1 , 0
  4469.3     .07       0    4995     .07       0  5002.1     .07       0
Bank Sta=4995,5002.1
XS Rating Curve= 0 ,0
Exp/Cntr=0.3,0.1

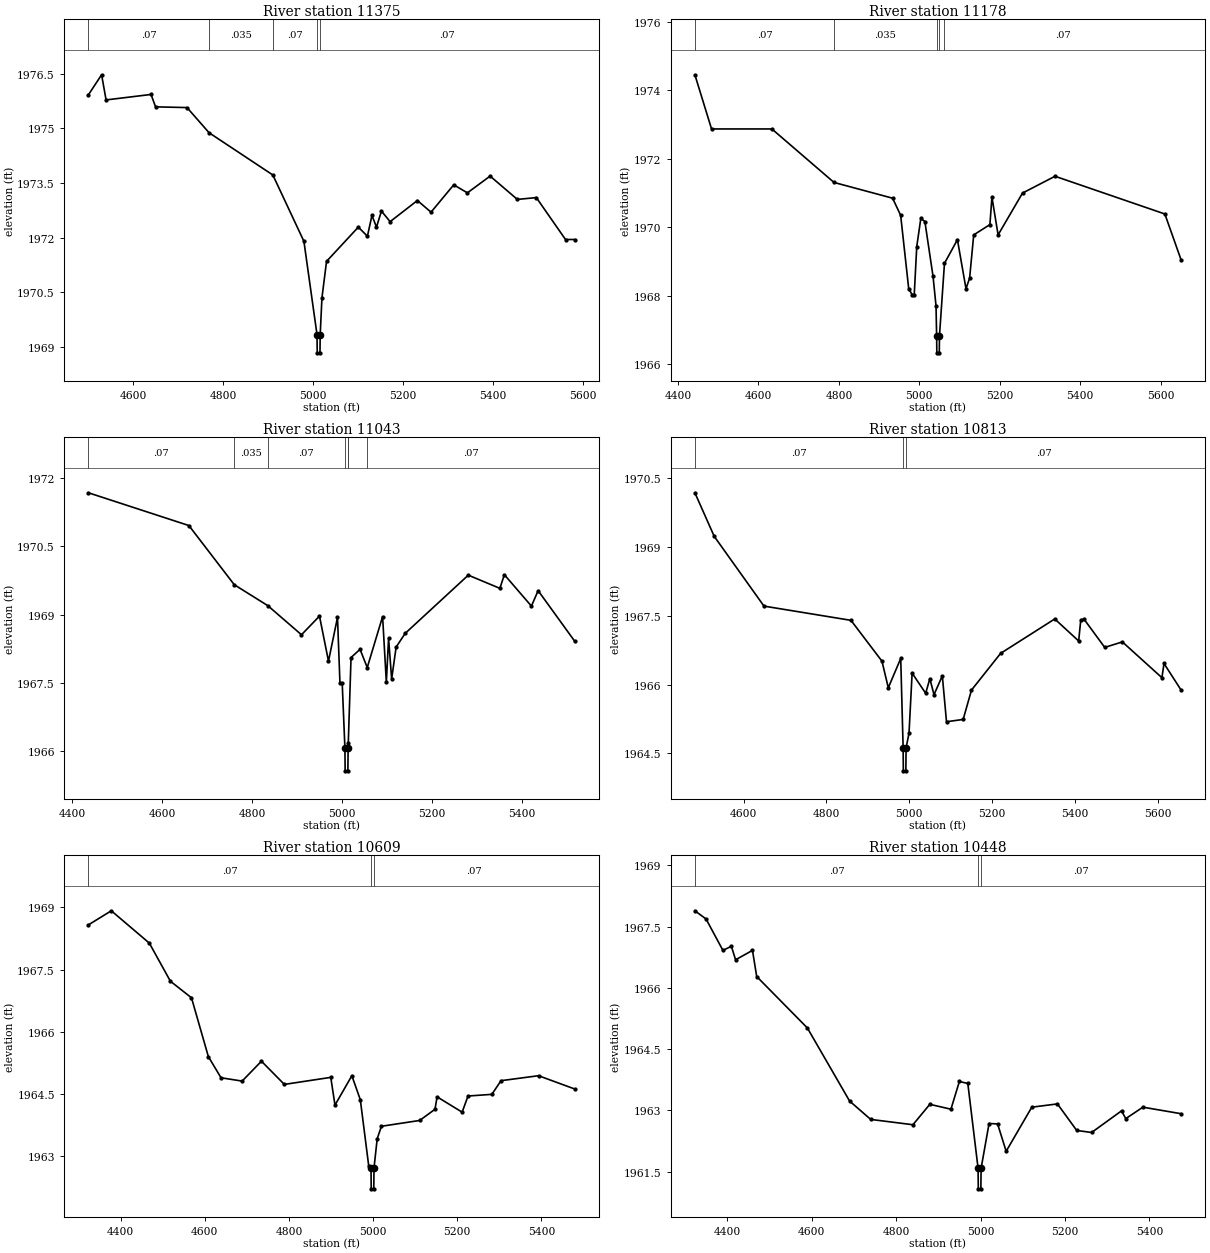
Type RM Length L Ch R = 1 ,11375   ,197,197,197
BEGIN DESCRIPTION:
Elm 01 22 11374.74
END DESCRIPTION:
XS GIS Cut Line= 3
      1527905.69      6805189.89      1528412.65      6805193.36
      1528981.03      6805110.19
#Sta/Elev= 30
    4500 1975.92  4529.3 1976.47  4539.3 1975.78  4639.3 1975.93  4649.3 1975.59
  4719.3 1975.57  4768.3 1974.88  4910.2 1973.72  4979.3  1971.9  5008.4 1969.34
  5008.9 1968.84    5015 1968.84  5015.5 1969.34  5019.4 1970.35  5029.6 1971.35
  5100.3 1972.29  5120.5 1972.04  5130.6 1972.61  5140.7 1972.29  5151.7 1972.73
    5171 1972.44  5231.7 1973.02    5262  1972.7  5312.5 1973.45  5342.9 1973.23
  5393.4 1973.69    5454 1973.05  5496.2  1973.1  5561.1 1971.95  5581.4 1971.95
#Mann= 5 ,-1 , 0
    4500     .07       0  4768.3    .035       0  4910.2     .07       0
  5008.4     .07       0  5015.5     .07       0
Bank Sta=5008.4,5015.5
XS Rating Curve= 0 ,0
Exp/Cntr=0.3,0.1

Type RM Length L Ch R = 1 ,11178   ,135,135,135
BEGIN DESCRIPTION:
Elm 01 22 11177.61
END DESCRIPTION:
XS GIS Cut Line= 3
      1527853.59      6805384.34      1528398.76      6805391.28
      1529054.98      6805294.06
#Sta/Elev= 30
    4442 1974.45  4483.4 1972.87  4633.4 1972.87  4787.8 1971.31  4933.5 1970.85
  4953.5 1970.35  4973.5 1968.21  4982.8 1968.02  4987.2 1968.02  4993.5 1969.44
  5003.6 1970.26  5013.7 1970.17    5034 1968.57  5041.4 1967.71  5042.9 1966.84
  5043.4 1966.34  5049.5 1966.34    5050 1966.84  5062.4 1968.95  5094.6 1969.64
  5115.9 1968.21  5124.9 1968.52  5135.1 1969.78  5175.3 1970.08  5180.4 1970.88
  5195.7 1969.78  5256.4    1971  5337.2 1971.49  5610.2 1970.39  5650.6 1969.05
#Mann= 5 ,-1 , 0
    4442     .07       0  4787.8    .035       0  5042.9    .035       0
    5050    .035       0  5062.4     .07       0
Bank Sta=5042.9,5050
XS Rating Curve= 0 ,0
Exp/Cntr=0.3,0.1

Type RM Length L Ch R = 1 ,11043   ,230,230,230
BEGIN DESCRIPTION:
Elm 01 22 11043.35
END DESCRIPTION:
XS GIS Cut Line= 3
      1527891.83      6805523.23      1528450.84      6805509.34
      1528970.82      6805478.14
#Sta/Elev= 30
  4436.2 1971.68  4659.4 1970.96  4760.2 1969.66  4834.7  1969.2  4909.5 1968.56
  4949.5 1968.97  4969.5 1967.98  4989.5 1968.94    4995 1967.49    5000 1967.49
    5006 1966.07  5006.5 1965.57  5012.6 1965.57  5013.1 1966.07  5013.5 1966.19
  5019.6 1968.06  5039.6 1968.24  5055.6 1967.84  5089.7 1968.96    5098 1967.52
    5103 1968.48  5109.8 1967.59  5119.8 1968.29  5139.8 1968.59  5280.1 1969.87
  5350.2 1969.58  5360.2 1969.88  5420.3 1969.19  5435.2 1969.53  5516.3 1968.42
#Mann= 7 ,-1 , 0
  4436.2     .07       0  4760.2    .035       0  4834.7     .07       0
    5006     .07       0  5013.1     .07       0  5013.5    .035       0
  5055.6     .07       0
Bank Sta=5006,5013.1
XS Rating Curve= 0 ,0
Exp/Cntr=0.3,0.1

Type RM Length L Ch R = 1 ,10813   ,204,204,204
BEGIN DESCRIPTION:
Elm 01 22 10813
END DESCRIPTION:
XS GIS Cut Line= 3
       1527888.3      6805710.72      1528398.76      6805724.61
      1529058.52      6805658.64
#Sta/Elev= 30
  4482.6 1970.18  4529.3 1969.23  4649.4 1967.71  4859.4  1967.4  4934.2 1966.51
  4949.5 1965.93  4979.5 1966.57  4985.3 1964.62  4985.8 1964.12  4991.9 1964.12
  4992.4 1964.62  4999.5 1964.94    5007 1966.25  5039.7 1965.81  5049.8 1966.13
  5059.8 1965.78  5079.9 1966.19    5090 1965.19  5130.2 1965.24  5150.3 1965.88
  5220.6 1966.68  5351.3 1967.43    5409 1966.95    5414  1967.4  5421.6 1967.43
  5471.9 1966.81  5514.5 1966.93    5610 1966.15    5615 1966.46  5656.3 1965.88
#Mann= 3 ,-1 , 0
  4482.6     .07       0  4985.3     .07       0  4992.4     .07       0
Bank Sta=4985.3,4992.4
XS Rating Curve= 0 ,0
Exp/Cntr=0.3,0.1

Type RM Length L Ch R = 1 ,10609   ,161,161,161
BEGIN DESCRIPTION:
Elm 01 22 10609.22
END DESCRIPTION:
XS GIS Cut Line= 3
      1527780.69       6805863.5      1528457.78      6805912.11
      1528930.03      6805849.61
#Sta/Elev= 30
  4323.7 1968.58  4378.1 1968.92  4468.4 1968.14  4518.5 1967.22  4568.6 1966.82
  4608.7  1965.4  4638.8 1964.89  4688.9 1964.81  4734.8 1965.29  4789.2 1964.73
  4899.5  1964.9  4909.5 1964.23  4949.6 1964.94  4969.7 1964.36  4989.7 1962.76
  4995.1 1962.71  4995.6 1962.21  5001.7 1962.21  5002.2 1962.71  5009.8 1963.42
  5019.9 1963.72  5110.7 1963.86  5147.1 1964.13  5152.1 1964.43  5211.6 1964.06
  5225.6 1964.45  5282.2 1964.49    5304 1964.82  5393.1 1964.94  5478.9 1964.62
#Mann= 3 ,-1 , 0
  4323.7     .07       0  4995.1     .07       0  5002.2     .07       0
Bank Sta=4995.1,5002.2
XS Rating Curve= 0 ,0
Exp/Cntr=0.3,0.1

Type RM Length L Ch R = 1 ,10448   ,228,228,228
BEGIN DESCRIPTION:
Elm 01 22 10447.76
END DESCRIPTION:
XS GIS Cut Line= 3
      1527728.63      6806068.36       1528405.7      6806057.95
      1528874.41      6805985.04
#Sta/Elev= 30
  4323.5 1967.89  4349.9 1967.69  4389.9 1966.92  4409.9 1967.02  4419.9 1966.69
  4459.9 1966.92  4469.9 1966.28  4589.9 1965.02  4689.9 1963.23  4739.9 1962.78
  4839.9 1962.65  4879.9 1963.15  4929.9 1963.03  4949.9 1963.71  4969.9 1963.66
  4994.2 1961.58  4994.7 1961.08  5000.8 1961.08  5001.3 1961.58  5020.2 1962.68
  5040.4 1962.67  5060.7    1962  5121.4 1963.08  5182.1 1963.16  5227.8 1962.51
  5263.1 1962.46  5333.9 1962.99    5344  1962.8  5384.5 1963.08    5475 1962.92
#Mann= 3 ,-1 , 0
  4323.5     .07       0  4994.2     .07       0  5001.3     .07       0
Bank Sta=4994.2,5001.3
XS Rating Curve= 0 ,0
Exp/Cntr=0.3,0.1

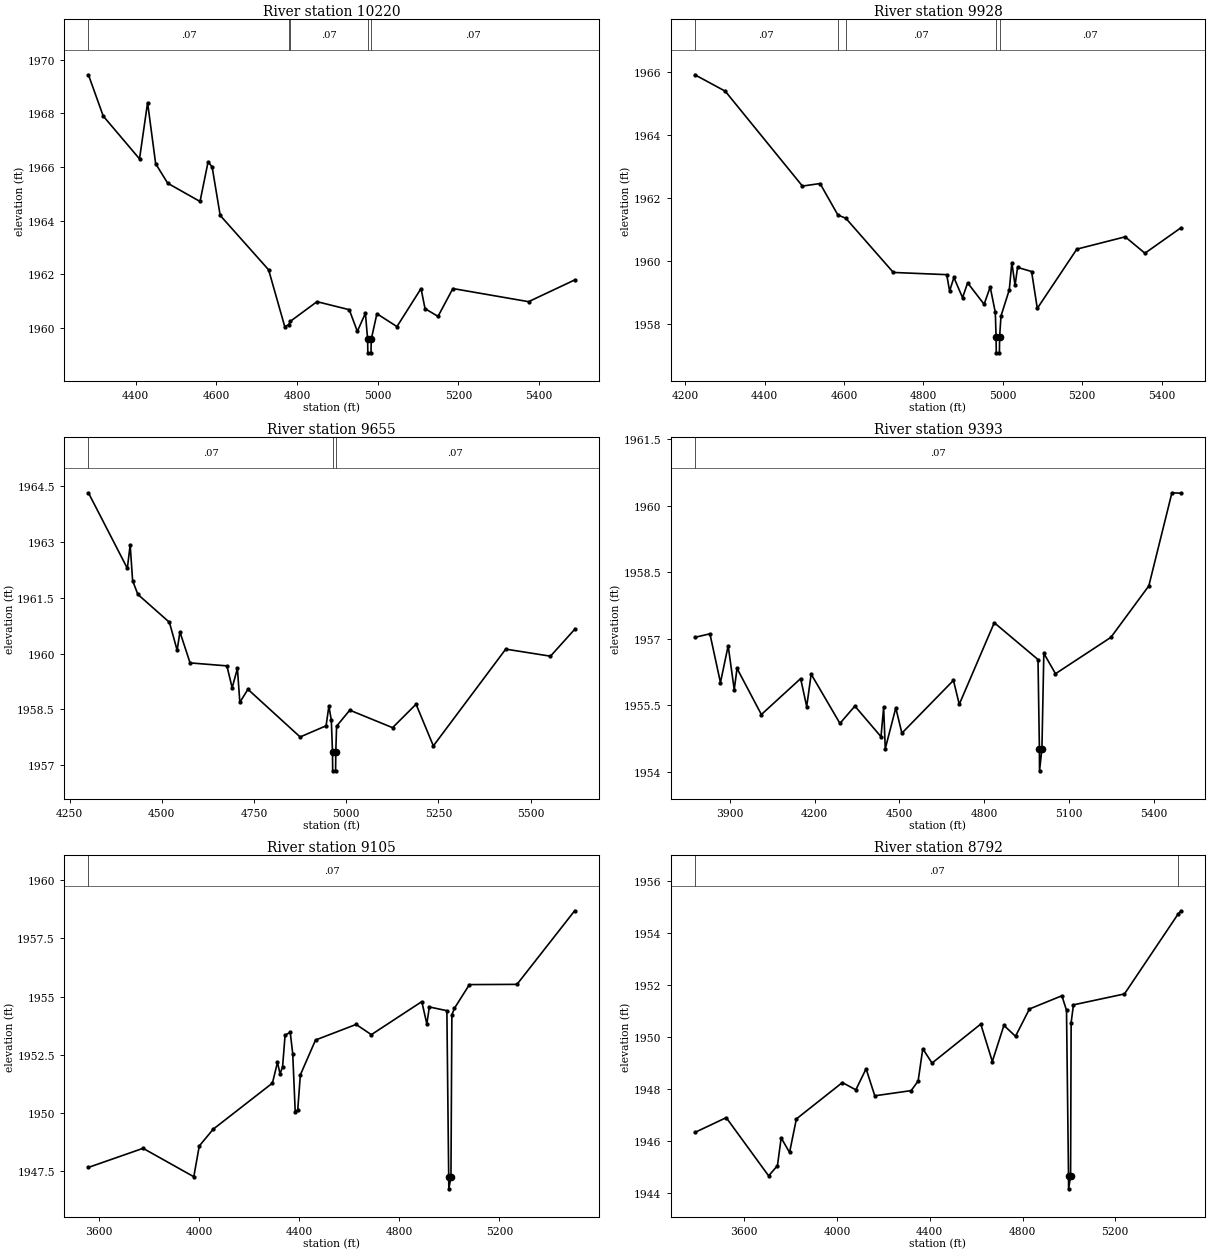
Type RM Length L Ch R = 1 ,10220   ,292,292,292
BEGIN DESCRIPTION:
Elm 01 22 10220.31
END DESCRIPTION:
XS GIS Cut Line= 3
      1527638.35      6806269.75      1528357.09      6806269.75
      1528810.59       6806093.2
#Sta/Elev= 30
  4282.7 1969.44  4319.4  1967.9  4409.4  1966.3  4429.4  1968.4  4449.4 1966.12
  4479.4 1965.39  4559.4 1964.71  4579.4 1966.19  4589.4    1966  4609.4 1964.19
  4729.4 1962.16  4769.4 1960.04  4779.1 1960.11  4783.6 1960.24  4849.4 1960.97
  4929.4 1960.67  4949.4 1959.86  4969.4 1960.54  4974.9 1959.56  4975.4 1959.06
  4983.3 1959.06  4983.8 1959.56  4997.9 1960.52  5047.6 1960.04  5107.3 1961.46
  5117.2 1960.71  5149.4 1960.42  5186.2 1961.46  5373.9 1960.97  5488.1 1961.78
#Mann= 5 ,-1 , 0
  4282.7     .07       0  4779.1     .16       0  4783.6     .07       0
  4974.9     .07       0  4983.8     .07       0
Bank Sta=4974.9,4983.8
XS Rating Curve= 0 ,0
Exp/Cntr=0.3,0.1

Type RM Length L Ch R = 1 ,9928    ,273,273,273
BEGIN DESCRIPTION:
Elm 01 22 9927.87
END DESCRIPTION:
XS GIS Cut Line= 3
      1527805.02        6806801.      1528489.03      6806509.34
      1528786.79      6806131.96
#Sta/Elev= 30
  4224.7 1965.92  4301.1  1965.4  4495.5 1962.39  4539.9 1962.47  4584.9 1961.47
  4604.7 1961.37  4724.4 1959.65  4858.8 1959.58  4866.1 1959.06  4876.9 1959.49
  4898.7 1958.85  4911.5 1959.32    4953 1958.64  4968.3 1959.19  4981.2 1958.38
  4983.1  1957.6  4983.6  1957.1  4991.5  1957.1    4992  1957.6  4995.5 1958.27
  5016.4  1959.1  5022.8 1959.96  5030.9 1959.24  5037.2 1959.81  5072.5 1959.68
  5086.9 1958.51  5186.5 1960.39  5308.2 1960.78  5357.9 1960.26    5449 1961.07
#Mann= 5 ,-1 , 0
  4224.7     .07       0  4584.9     .16       0  4604.7     .07       0
  4983.1     .07       0    4992     .07       0
Bank Sta=4983.1,4992
XS Rating Curve= 0 ,0
Exp/Cntr=0.3,0.1

Type RM Length L Ch R = 1 ,9655    ,262,262,262
BEGIN DESCRIPTION:
Elm 01 22 9655.16
END DESCRIPTION:
XS GIS Cut Line= 3
      1528114.03      6807266.28      1528565.42      6806741.98
      1528784.17      6806155.17
#Sta/Elev= 30
  4301.2 1964.32  4406.7 1962.29  4414.4 1962.92    4421 1961.96  4435.2 1961.59
  4520.8 1960.84  4541.7 1960.09  4549.3 1960.58  4576.8 1959.75  4676.6 1959.67
  4690.9 1959.08  4705.1  1959.6  4711.7 1958.69  4733.6 1959.04  4875.2 1957.76
  4945.5 1958.06  4953.1 1958.59  4959.7 1958.21  4962.9 1957.35  4963.4 1956.85
  4971.3 1956.85  4971.8 1957.35    4974 1958.05  5009.7 1958.48  5125.7 1958.01
  5189.4 1958.64  5236.3 1957.52  5432.5 1960.12  5553.8 1959.93  5619.3 1960.65
#Mann= 3 ,-1 , 0
  4301.2     .07       0  4962.9     .07       0  4971.8     .07       0
Bank Sta=4962.9,4971.8
XS Rating Curve= 0 ,0
Exp/Cntr=0.3,0.1

Type RM Length L Ch R = 1 ,9393    ,288,288,288
BEGIN DESCRIPTION:
Elm 01 22 9393.13
END DESCRIPTION:
XS GIS Cut Line= 3
      1529280.91      6807787.71       1528781.3      6806816.52
      1528936.95      6806207.25
#Sta/Elev= 30
  3776.4 1957.03  3829.6 1957.11  3866.9 1956.01  3894.2 1956.84  3915.7 1955.85
  3925.6 1956.33  4011.7 1955.29  4150.7  1956.1  4172.2 1955.47    4188  1956.2
  4289.8 1955.09  4342.7 1955.48  4435.2 1954.79  4444.5 1955.45  4450.3 1954.52
  4487.5 1955.44  4509.1 1954.87  4691.6 1956.06  4712.2 1955.52  4836.1 1957.36
  4990.9 1956.53  4995.8 1954.52  4996.3 1954.02  5004.8 1954.52  5011.5 1956.67
  5052.8 1956.21  5248.9 1957.03  5383.1 1958.19  5464.9 1960.29  5497.4 1960.28
#Mann= 1 ,-1 , 0
  3776.4     .07       0
Bank Sta=4995.8,5004.8
XS Rating Curve= 0 ,0
Exp/Cntr=0.3,0.1

Type RM Length L Ch R = 1 ,9105    ,313,313,313
BEGIN DESCRIPTION:
Elm 01 22 9105.13
END DESCRIPTION:
XS GIS Cut Line= 3
       1529103.5      6808130.27      1529065.42      6806873.92
      1529100.08      6806187.82
#Sta/Elev= 30
    3557 1947.67  3775.5 1948.49  3978.3 1947.27  4000.2 1948.59  4055.8 1949.31
  4292.6 1951.29  4312.9 1952.18  4323.1 1951.69  4333.2 1951.98  4343.3 1953.35
  4363.8 1953.47  4373.8 1952.56  4383.9 1950.03    4394 1950.15  4404.2 1951.64
    4465 1953.14  4627.3 1953.81  4688.1 1953.37  4889.9 1954.79    4910 1953.83
    4920 1954.56  4990.1  1954.4  4997.4 1947.25  4997.9 1946.75  5006.4 1947.25
  5010.1 1954.22  5020.1  1954.5  5080.2 1955.52  5270.4 1955.53  5500.9 1958.69
#Mann= 1 ,-1 , 0
    3557     .07       0
Bank Sta=4997.4,5006.4
XS Rating Curve= 0 ,0
Exp/Cntr=0.3,0.1

Type RM Length L Ch R = 1 ,8792    ,446,446,446
BEGIN DESCRIPTION:
Elm 01 22 8791.72
END DESCRIPTION:
XS GIS Cut Line= 3
      1528846.15      6808210.93      1529355.41       6806816.6
      1529360.56      6806203.74
#Sta/Elev= 30
  3386.7 1946.33  3521.9  1946.9  3704.8 1944.66  3742.8 1945.05  3758.9 1946.12
  3795.1 1945.56  3824.5 1946.85  4022.8 1948.25    4081 1947.97  4125.2 1948.78
  4162.7 1947.74  4319.7 1947.94  4349.7 1948.31  4369.7 1949.55  4409.7    1949
  4619.7  1950.5  4669.7 1949.06  4719.7 1950.45  4769.7 1950.03  4829.7 1951.08
  4969.7 1951.59  4989.7 1951.03  4998.3 1944.66  4998.8 1944.16  5007.3 1944.66
  5009.7 1950.56  5019.7 1951.24  5239.7 1951.66  5470.7 1954.73    5484 1954.86
#Mann= 2 ,-1 , 0
  3386.7     .07       0  5470.7     .16       0
Bank Sta=4998.3,5007.3
XS Rating Curve= 0 ,0
Exp/Cntr=0.3,0.1

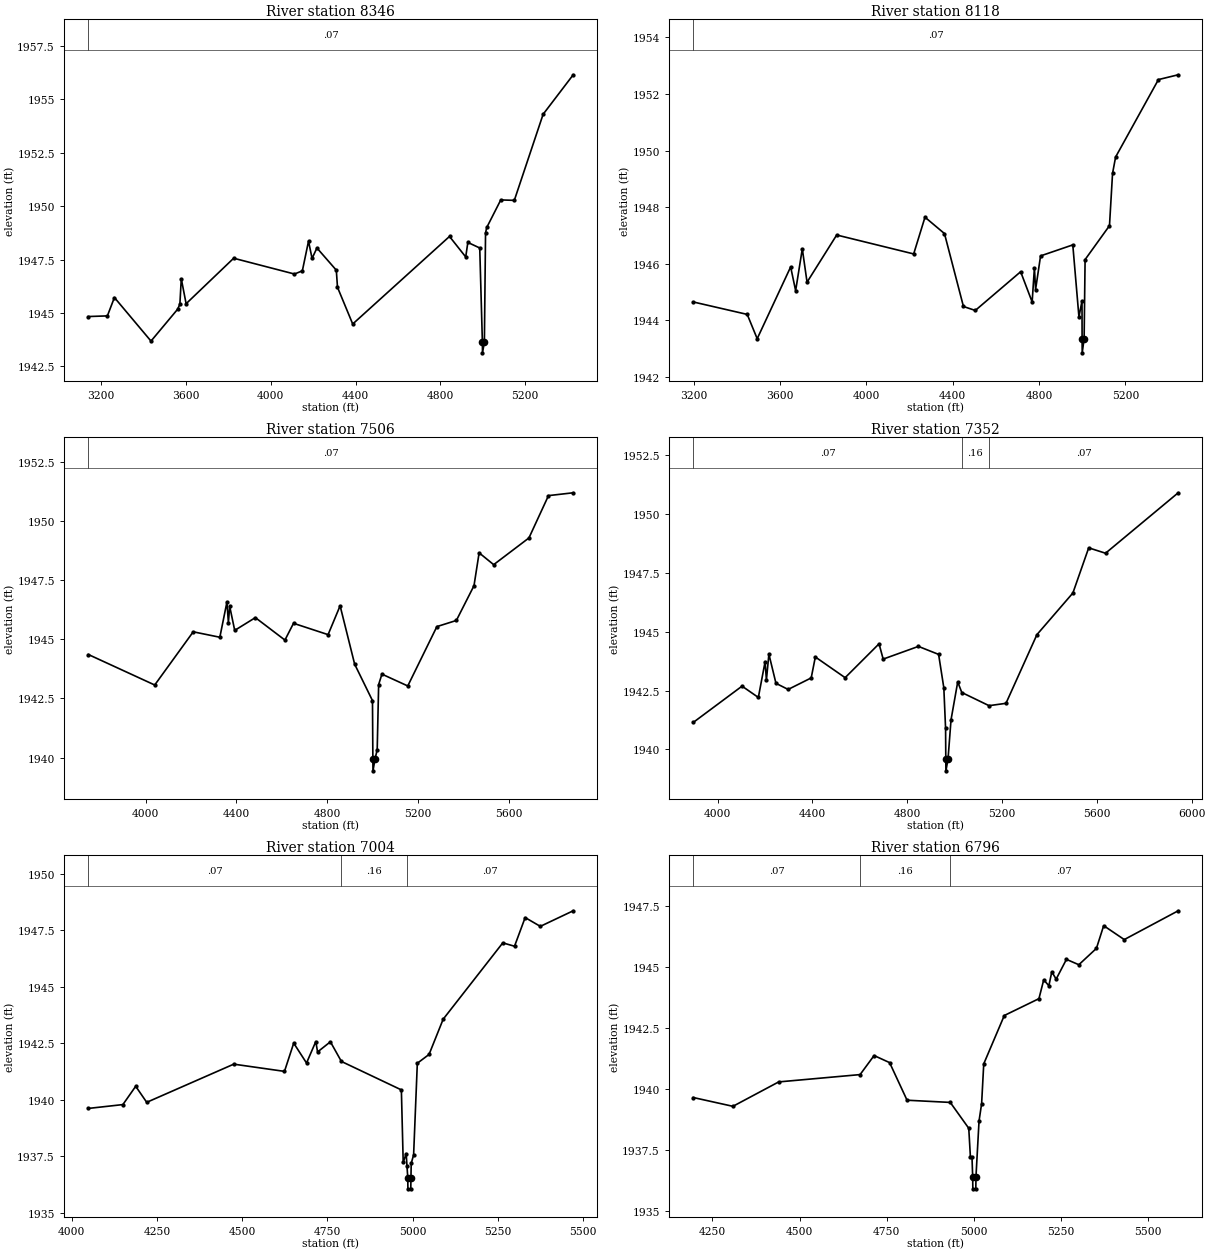
Type RM Length L Ch R = 1 ,8346    ,228,228,228
BEGIN DESCRIPTION:
Elm 01 22 8346.06
END DESCRIPTION:
XS GIS Cut Line= 3
      1528567.67      6807958.54      1529687.54      6806730.07
      1529867.18      6806131.97
#Sta/Elev= 30
  3139.3 1944.83  3229.1 1944.86  3262.2 1945.72  3434.8 1943.68  3560.2 1945.17
    3571 1945.41  3577.6  1946.6  3600.4 1945.43  3824.7 1947.56  4111.5 1946.82
  4148.6 1946.97  4177.7 1948.36  4194.4 1947.55  4217.3 1948.04  4308.8    1947
  4314.3  1946.2  4386.1 1944.48  4842.6 1948.58  4919.1 1947.62  4929.1  1948.3
  4985.2 1948.04  4997.7 1943.63  4998.2 1943.13  5007.1 1943.63  5012.6 1948.75
  5018.3    1949  5084.4 1950.29  5148.3 1950.27  5284.1  1954.3  5426.1 1956.15
#Mann= 1 ,-1 , 0
  3139.3     .07       0
Bank Sta=4997.7,5007.1
XS Rating Curve= 0 ,0
Exp/Cntr=0.3,0.1

Type RM Length L Ch R = 1 ,8118    ,612,612,612
BEGIN DESCRIPTION:
Elm 01 22 8117.96
END DESCRIPTION:
XS GIS Cut Line= 3
      1528493.04      6807861.81      1529745.98      6806828.78
      1530214.76      6806419.03
#Sta/Elev= 30
    3198 1944.64  3447.7  1944.2  3493.9 1943.34  3648.9 1945.88    3672 1945.04
  3702.9 1946.52  3724.9 1945.34  3862.2 1947.01  4218.9 1946.34  4271.3 1947.64
  4361.6 1947.06  4449.5 1944.48  4504.4 1944.34  4714.5 1945.71  4767.8 1944.64
  4778.3 1945.85  4783.7 1945.08  4806.8 1946.27  4956.1 1946.66  4984.6 1944.11
  4998.8 1944.68  4999.2 1943.34  4999.7 1942.84  5008.6 1943.34  5013.1 1946.14
  5126.1 1947.34  5140.3 1949.19  5154.5 1949.77  5352.9 1952.51  5444.5 1952.68
#Mann= 1 ,-1 , 0
    3198     .07       0
Bank Sta=4999.2,5008.6
XS Rating Curve= 0 ,0
Exp/Cntr=0.3,0.1

Type RM Length L Ch R = 1 ,7506    ,154,154,154
BEGIN DESCRIPTION:
Elm 01 22 7506.49
END DESCRIPTION:
XS GIS Cut Line= 3
      1528934.77      6808228.23      1529627.92       6807363.5
      1530262.53      6806552.04
#Sta/Elev= 30
  3746.8 1944.36  4039.5 1943.07  4209.3 1945.32  4326.7 1945.09    4358 1946.58
  4364.4 1945.71  4370.1  1946.4  4392.3 1945.38  4483.4 1945.92  4613.8 1944.97
  4651.6 1945.68  4804.1  1945.2  4857.1 1946.42  4921.3 1943.95  4999.9 1942.41
  5001.6 1939.94  5002.1 1939.44    5011 1939.94  5020.7 1940.33  5027.1 1943.09
  5041.5 1943.53  5155.5 1943.03  5283.9 1945.54  5369.8  1945.8  5447.6 1947.27
  5470.2 1948.66  5534.4 1948.16  5689.9 1949.29  5776.1 1951.08  5885.2  1951.2
#Mann= 1 ,-1 , 0
  3746.8     .07       0
Bank Sta=5001.6,5011
XS Rating Curve= 0 ,0
Exp/Cntr=0.3,0.1

Type RM Length L Ch R = 1 ,7352    ,348,348,348
BEGIN DESCRIPTION:
Elm 01 22 7351.93
END DESCRIPTION:
XS GIS Cut Line= 4
      1528905.75      6808002.09       1529752.4      6807469.26
      1529798.06      6807370.45      1530298.08      6806578.75
#Sta/Elev= 30
  3897.8 1941.15  4103.3 1942.69  4172.1 1942.21  4200.6 1943.73  4206.1 1942.95
  4216.6 1944.05  4246.4 1942.81  4297.8 1942.55  4395.1 1943.04  4412.5 1943.93
  4538.2 1943.05  4681.3 1944.49  4698.7 1943.84  4847.4 1944.38  4932.6 1944.04
  4954.6 1942.62    4962 1940.89  4962.9 1939.59  4963.4 1939.09  4972.3 1939.59
    4985 1941.26  5013.2 1942.87  5030.4 1942.42  5145.3 1941.86  5216.8 1941.96
  5347.4 1944.88  5499.1 1946.65  5565.8 1948.57  5636.8 1948.34  5943.4 1950.91
#Mann= 3 ,-1 , 0
  3897.8     .07       0  5030.4     .16       0  5145.3     .07       0
Bank Sta=4962.9,4972.3
XS Rating Curve= 0 ,0
Exp/Cntr=0.3,0.1

Type RM Length L Ch R = 1 ,7004    ,208,208,208
BEGIN DESCRIPTION:
Elm 01 22 7003.8
END DESCRIPTION:
XS GIS Cut Line= 4
      1529343.39      6807758.34      1529956.41       6807484.7
      1530058.48      6807318.36      1530280.35      6806808.75
#Sta/Elev= 30
  4048.7 1939.61    4150 1939.78  4187.6 1940.59  4219.9 1939.88  4475.2 1941.57
    4624 1941.25  4651.1  1942.5  4688.7 1941.62  4715.9 1942.57  4721.1 1942.11
  4758.7 1942.56    4791 1941.69  4966.9 1940.43  4972.3 1937.22    4981 1937.61
  4983.4 1937.06  4985.6 1936.55  4986.1 1936.05  4994.5 1936.05    4995 1936.55
  4995.8 1937.18  5002.8 1937.55  5013.7 1941.61  5048.1    1942  5089.5 1943.56
  5264.4 1946.94  5298.8 1946.79    5330 1948.06  5374.5 1947.67    5471 1948.36
#Mann= 3 ,-1 , 0
  4048.7     .07       0    4791     .16       0  4983.4     .07       0
Bank Sta=4985.6,4995
XS Rating Curve= 0 ,0
Exp/Cntr=0.3,0.1

Type RM Length L Ch R = 1 ,6796    ,105,105,105
BEGIN DESCRIPTION:
Elm 01 22 6796.02
END DESCRIPTION:
XS GIS Cut Line= 4
      1529655.74      6807699.72      1530172.35      6807550.15
      1530263.34      6807304.48      1530606.65      6806822.45
#Sta/Elev= 30
    4195 1939.66  4308.6  1939.3    4440  1940.3  4673.6  1940.6  4713.8 1941.38
  4758.3 1941.09  4808.4 1939.55  4932.4 1939.46  4985.5  1938.4  4990.3 1937.21
  4994.8 1937.21  4996.7 1936.42  4997.2 1935.92  5005.7 1935.92  5006.2 1936.42
    5015  1938.7  5022.4 1939.41  5028.5 1941.04  5087.5 1943.02  5186.9 1943.71
  5200.6 1944.48  5215.4 1944.24  5223.8 1944.81  5236.3 1944.51  5265.8 1945.32
  5301.4  1945.1  5351.9 1945.77  5372.7  1946.7  5431.8 1946.13  5586.6 1947.31
#Mann= 3 ,-1 , 0
    4195     .07       0  4673.6     .16       0  4932.4     .07       0
Bank Sta=4996.7,5006.2
XS Rating Curve= 0 ,0
Exp/Cntr=0.3,0.1

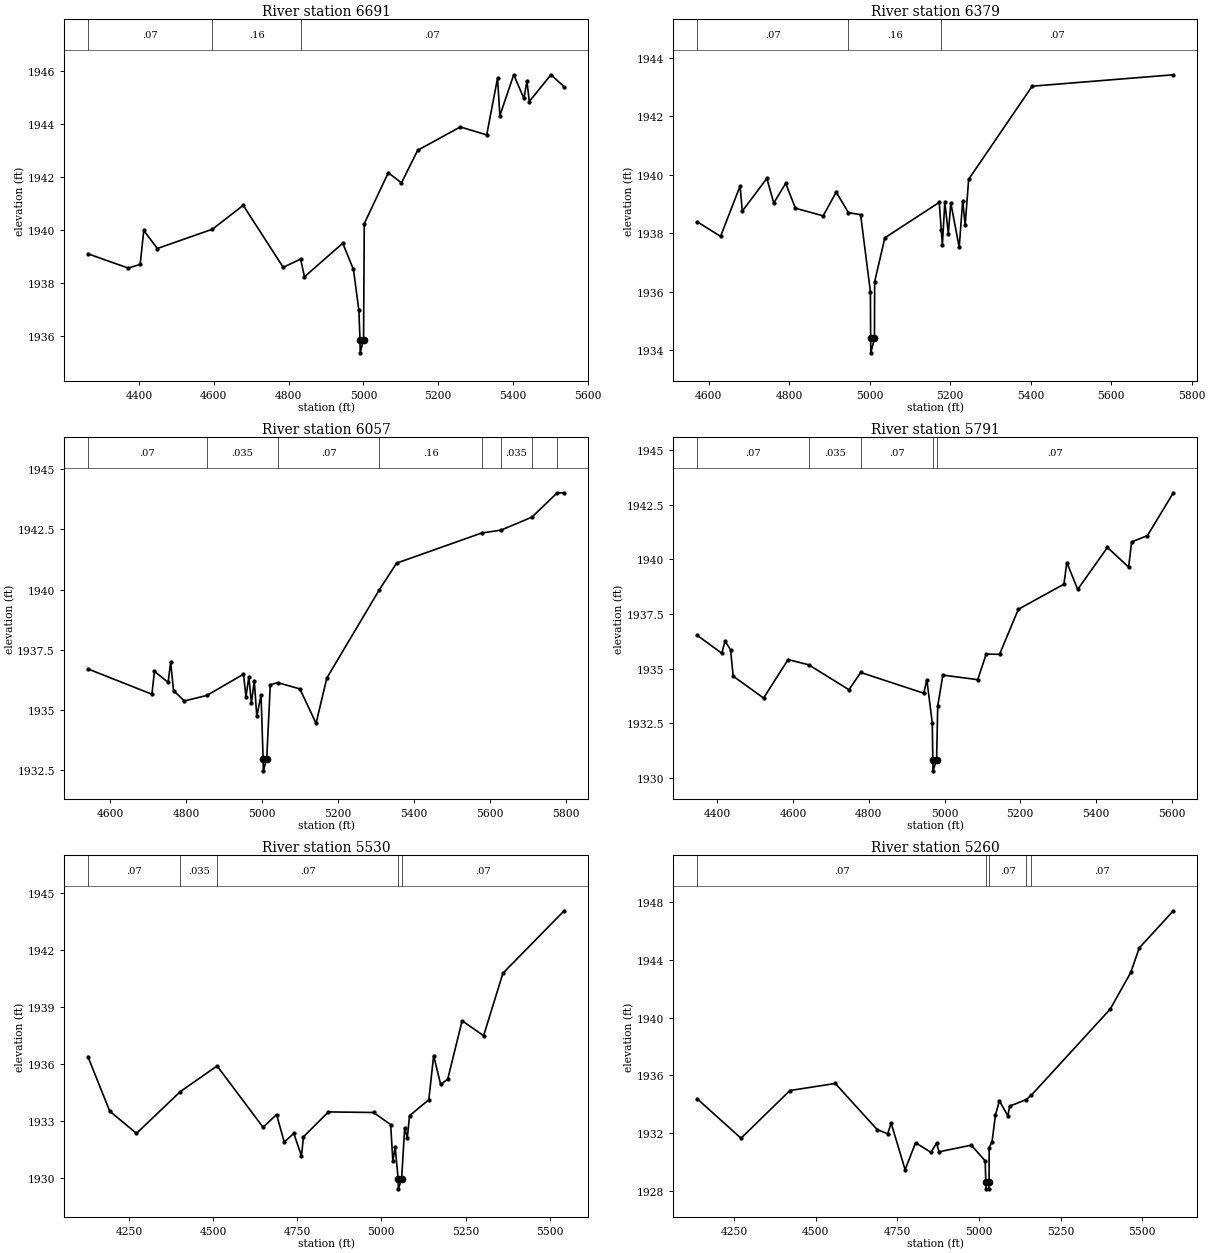
Type RM Length L Ch R = 1 ,6691    ,312,312,312
BEGIN DESCRIPTION:
Elm 01 22 6690.51
END DESCRIPTION:
XS GIS Cut Line= 4
      1529830.68      6807760.68      1530210.12      6807645.37
       1530280.7      6807443.36      1530690.03      6806923.03
#Sta/Elev= 30
  4263.8  1939.1  4371.6 1938.56  4403.4  1938.7  4413.1 1939.98  4449.4  1939.3
  4596.7 1940.03  4678.8 1940.93  4785.6 1938.59  4832.3  1938.9  4842.4 1938.23
  4944.8  1939.5  4973.4 1938.51  4987.9 1936.96  4990.9 1935.86  4991.4 1935.36
  5000.4 1935.86  5002.3 1940.24  5066.5 1942.16  5101.7 1941.78  5145.1 1943.01
    5259 1943.89  5329.5 1943.59  5358.4 1945.73  5364.7 1944.32  5401.7 1945.86
  5428.9 1944.97    5437 1945.62  5443.3 1944.85  5501.1 1945.86  5536.4 1945.41
#Mann= 3 ,-1 , 0
  4263.8     .07       0  4596.7     .16       0  4832.3     .07       0
Bank Sta=4990.9,5000.4
XS Rating Curve= 0 ,0
Exp/Cntr=0.3,0.1

Type RM Length L Ch R = 1 ,6379    ,322,322,322
BEGIN DESCRIPTION:
Elm 01 22 6379.3
END DESCRIPTION:
XS GIS Cut Line= 4
      1530017.83      6807893.41      1530285.08      6807682.82
      1530322.37       6807589.2      1530748.97      6806982.25
#Sta/Elev= 30
  4571.6  1938.4  4629.8  1937.9  4678.4 1939.62  4683.8 1938.76  4744.8 1939.88
    4762 1939.04  4791.6 1939.71  4815.9 1938.86  4884.7  1938.6    4917 1939.41
  4947.4 1938.71  4977.7 1938.64    5002 1936.01  5002.6 1934.42  5003.1 1933.92
  5012.1 1934.42  5012.6 1936.35  5037.9 1937.85    5173 1939.06    5178 1938.13
  5180.8 1937.61  5186.9 1939.07  5195.6 1937.99  5201.7 1939.04  5222.6 1937.53
  5231.3 1939.12  5237.4 1938.29  5246.1 1939.85  5403.8 1943.03  5754.5 1943.42
#Mann= 3 ,-1 , 0
  4571.6     .07       0  4947.4     .16       0    5178     .07       0
Bank Sta=5002.6,5012.1
XS Rating Curve= 0 ,0
Exp/Cntr=0.3,0.1

Type RM Length L Ch R = 1 ,6057    ,266,266,266
BEGIN DESCRIPTION:
Elm 01 22 6056.87
END DESCRIPTION:
XS GIS Cut Line= 4
      1530232.86      6808062.31      1530246.74      6808055.48
      1530576.27      6807763.68      1531128.33      6807188.18
#Sta/Elev= 30
  4541.5 1936.71  4709.9 1935.66  4716.6 1936.61  4752.6 1936.15  4759.2    1937
  4766.8 1935.81  4795.1 1935.38  4854.6 1935.61  4950.8 1936.49  4957.5 1935.56
    4965 1936.39  4971.7 1935.29  4979.2 1936.22  4985.9 1934.74  4997.1 1935.63
  5002.5 1932.98    5003 1932.48    5012 1932.98  5021.4 1936.05  5040.7 1936.14
  5099.3 1935.88  5141.8 1934.45  5170.1 1936.33  5308.1 1939.99  5353.8  1941.1
  5577.6 1942.35  5628.5 1942.47  5709.9 1943.01  5775.8 1944.01  5794.6 1944.02
#Mann= 8 ,-1 , 0
  4541.5     .07       0  4854.6    .035       0  5040.7     .07       0
  5308.1     .16       0  5577.6     .07       0  5628.5    .035       0
  5709.9     .07       0  5775.8    .035       0
Bank Sta=5002.5,5012
XS Rating Curve= 0 ,0
Exp/Cntr=0.3,0.1

Type RM Length L Ch R = 1 ,5791    ,261,261,261
BEGIN DESCRIPTION:
Elm 01 22 5790.84
END DESCRIPTION:
XS GIS Cut Line= 3
      1530258.55      6808141.29      1530763.77      6807849.61
      1531184.82      6807322.01
#Sta/Elev= 30
  4346.2 1936.53  4411.4 1935.71    4420 1936.26  4434.5 1935.87  4441.5 1934.66
  4521.9 1933.66  4586.6 1935.42  4641.1 1935.18  4747.4 1934.04  4778.5 1934.83
  4945.2 1933.88  4953.2  1934.5  4967.6 1932.52    4969 1930.83  4969.5 1930.33
    4979 1930.83    4982  1933.3  4995.6 1934.71  5087.7  1934.5  5110.1 1935.67
  5145.4 1935.66    5195 1937.72  5315.5 1938.87  5323.1 1939.86  5351.9 1938.63
  5430.4 1940.55  5486.4 1939.65  5494.4  1940.8  5536.1 1941.09  5604.6 1943.05
#Mann= 5 ,-1 , 0
  4346.2     .07       0  4641.1    .035       0  4778.5     .07       0
    4969     .07       0    4979     .07       0
Bank Sta=4969,4979
XS Rating Curve= 0 ,0
Exp/Cntr=0.3,0.1

Type RM Length L Ch R = 1 ,5530    ,270,270,270
BEGIN DESCRIPTION:
Elm 01 22 5529.56
END DESCRIPTION:
XS GIS Cut Line= 3
      1530305.41      6808232.44       1530904.4      6807951.18
      1531385.09      6807371.75
#Sta/Elev= 30
  4128.3 1936.37  4193.1  1933.5  4272.6 1932.33  4402.7 1934.53    4512 1935.88
  4648.6 1932.65  4688.7 1933.32  4711.5 1931.87  4739.8 1932.33  4762.7 1931.14
  4768.6 1932.15  4842.7 1933.46  4976.8 1933.43  5027.6 1932.79  5034.1 1930.87
    5041 1931.59    5050 1929.91  5050.5 1929.41    5060 1929.91  5069.3 1932.63
  5077.1 1932.08  5083.6 1933.26  5140.9  1934.1  5155.3 1936.42  5176.1 1934.91
    5197 1935.18  5239.9 1938.26  5303.7 1937.47    5361 1940.76  5542.9 1944.05
#Mann= 5 ,-1 , 0
  4128.3     .07       0  4402.7    .035       0    4512     .07       0
    5050     .07       0    5060     .07       0
Bank Sta=5050,5060
XS Rating Curve= 0 ,0
Exp/Cntr=0.3,0.1

Type RM Length L Ch R = 1 ,5260    ,191,191,191
BEGIN DESCRIPTION:
Elm 01 22 5260.03
END DESCRIPTION:
XS GIS Cut Line= 3
      1530339.29      6808287.12      1531099.71      6807998.05
      1531710.86        6807790.
#Sta/Elev= 30
  4136.5 1934.37    4271 1931.63  4420.8 1934.94  4559.8 1935.43  4688.2 1932.23
  4720.3 1931.94    4731 1932.68  4773.8 1929.45  4805.9 1931.32  4852.8 1930.65
  4870.1 1931.29  4877.6 1930.69  4976.7 1931.15    5019 1930.06    5021 1928.62
  5021.5 1928.12  5030.5 1928.12    5031 1928.62  5031.3 1930.97  5040.1 1931.39
  5050.7 1933.25  5062.6 1934.23  5088.7 1933.18    5094 1933.86  5143.8  1934.3
  5160.3 1934.61  5402.3 1940.59  5465.1 1943.13  5491.1 1944.83  5595.6 1947.41
#Mann= 5 ,-1 , 0
  4136.5     .07       0    5021     .07       0    5031     .07       0
  5143.8    .035       0  5160.3     .07       0
Bank Sta=5021,5031
XS Rating Curve= 0 ,0
Exp/Cntr=0.3,0.1