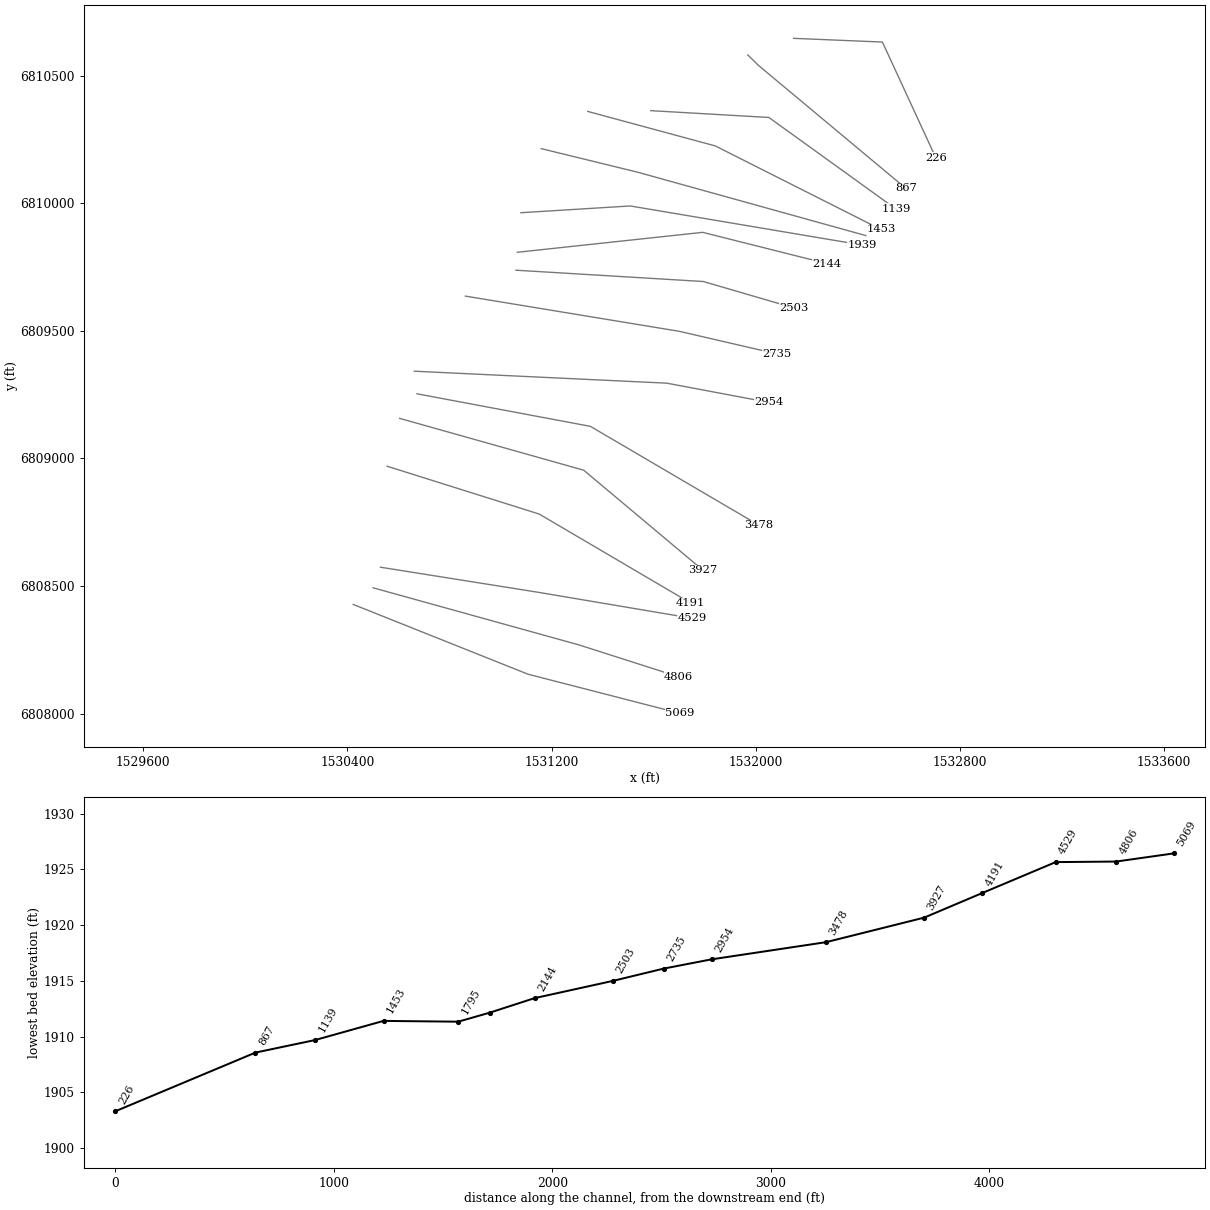
HEC-RAS study Elm 01 22.prj: Elm 01 22 Base Level Engineering

--- Elm 01 22.g01 (geometry) --- (continued)

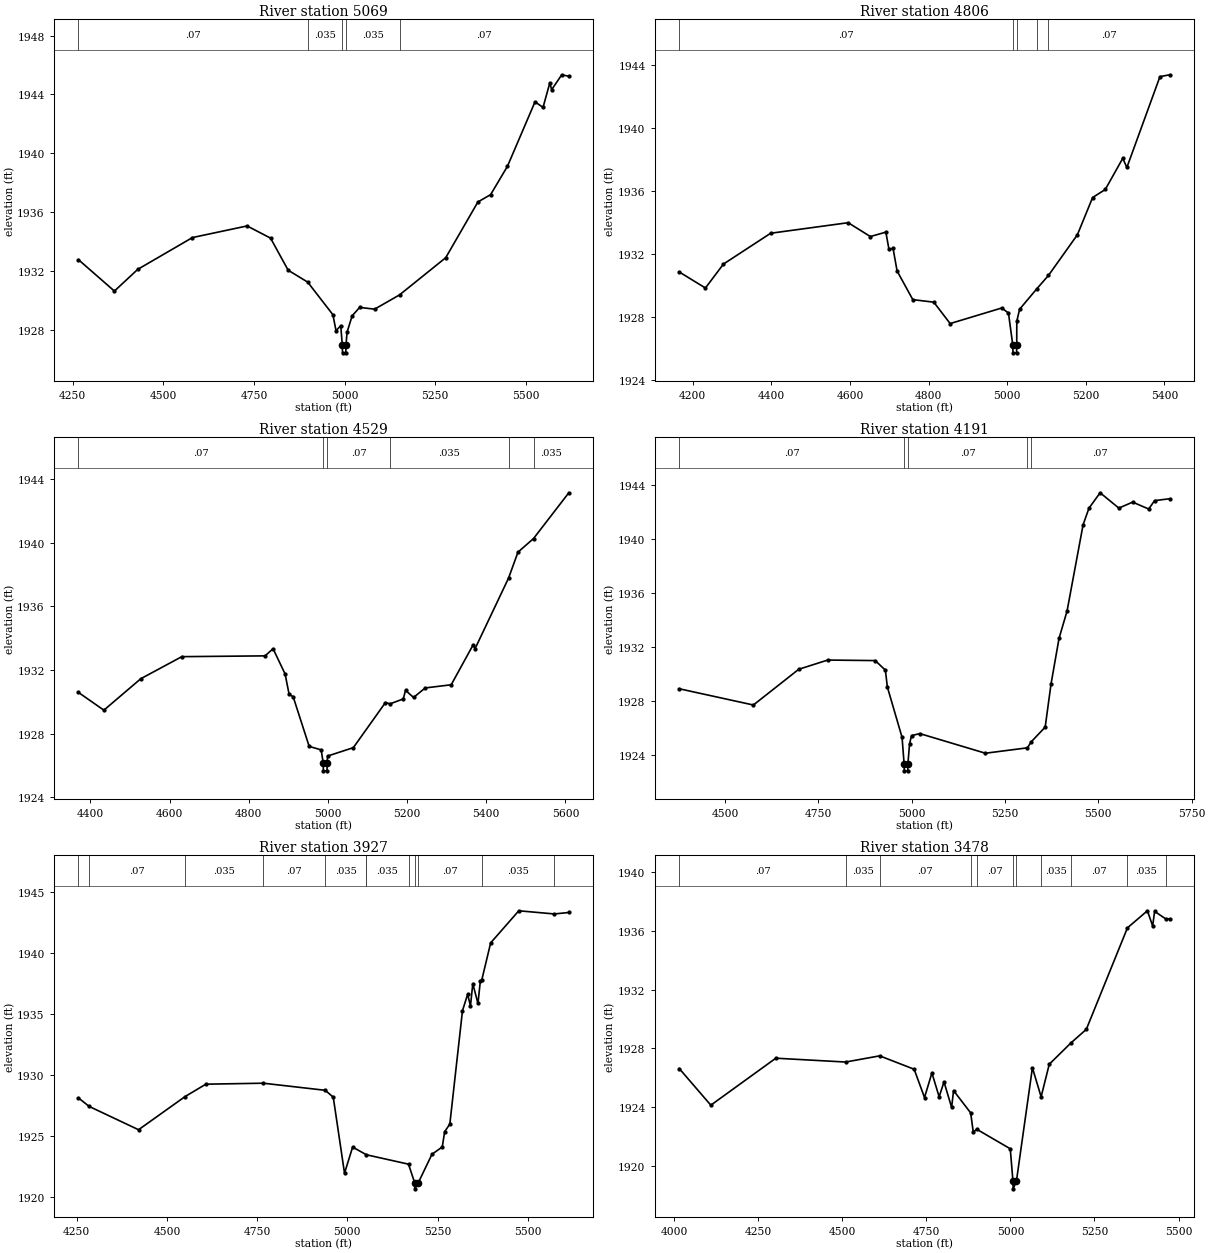
Type RM Length L Ch R = 1 ,5069    ,263,263,263
BEGIN DESCRIPTION:
Elm 01 22 5068.83
END DESCRIPTION:
XS GIS Cut Line= 3
      1530422.67      6808427.72      1531107.52       6808154.3
      1531703.83      6808000.67
#Sta/Elev= 30
  4265.5 1932.77  4364.9 1930.63  4429.5 1932.11  4580.3 1934.27    4731 1935.06
  4795.8 1934.23  4844.3 1932.05  4898.2 1931.24  4967.9 1929.02  4976.4 1927.93
  4989.4 1928.28  4993.8 1926.93  4994.3 1926.43  5003.4 1926.43  5003.9 1926.93
  5006.8 1927.83    5021 1928.95  5041.6 1929.52  5082.9  1929.4  5151.6 1930.37
  5279.1  1932.9  5367.9 1936.69    5403 1937.19  5449.3 1939.11  5525.5  1943.5
  5547.6 1943.12  5566.2 1944.78  5571.4 1944.33  5599.3 1945.34  5618.7 1945.24
#Mann= 5 ,-1 , 0
  4265.5     .07       0  4898.2    .035       0  4993.8    .035       0
  5003.9    .035       0  5151.6     .07       0
Bank Sta=4993.8,5003.9
XS Rating Curve= 0 ,0
Exp/Cntr=0.3,0.1

Type RM Length L Ch R = 1 ,4806    ,277,277,277
BEGIN DESCRIPTION:
Elm 01 22 4806.12
END DESCRIPTION:
XS GIS Cut Line= 3
      1530500.73      6808492.85      1531308.05      6808268.89
      1531698.63       6808143.9
#Sta/Elev= 30
  4165.5 1930.84  4232.2 1929.82    4278 1931.34  4398.2  1933.3  4595.4 1933.97
  4651.9 1933.09  4691.3 1933.37  4699.2 1932.28  4709.6 1932.34  4719.9  1930.9
  4759.9 1929.08  4813.3 1928.92  4854.9 1927.56  4986.2 1928.55  5003.3 1928.23
  5014.2  1926.2  5014.7  1925.7  5023.8  1925.7  5024.3  1926.2  5024.5 1927.71
  5031.6 1928.47  5075.4 1929.77  5105.1 1930.62  5178.6  1933.2  5217.4 1935.57
  5249.6 1936.08  5294.1 1938.06  5304.6 1937.48  5388.7 1943.25  5413.4 1943.37
#Mann= 5 ,-1 , 0
  4165.5     .07       0  5014.2     .07       0  5024.3     .07       0
  5075.4    .035       0  5105.1     .07       0
Bank Sta=5014.2,5024.3
XS Rating Curve= 0 ,0
Exp/Cntr=0.3,0.1

Type RM Length L Ch R = 1 ,4529    ,338,338,338
BEGIN DESCRIPTION:
Elm 01 22 4529.39
END DESCRIPTION:
XS GIS Cut Line= 3
      1530529.36      6808573.58       1531151.8      6808474.61
      1531751.65      6808373.34
#Sta/Elev= 30
  4369.8 1930.59  4434.2 1929.47  4527.4 1931.45    4631 1932.84  4841.3 1932.89
  4861.5 1933.34  4891.9 1931.75    4902 1930.47  4912.2 1930.32  4952.7 1927.19
    4983 1926.97  4988.1 1926.15  4988.6 1925.65  4997.7 1925.65  4998.2 1926.15
  4999.1 1926.58  5064.2 1927.11  5145.3 1929.95  5157.2 1929.87  5190.4 1930.18
    5196 1930.72  5216.3 1930.27  5245.8 1930.87  5311.4 1931.07  5366.7 1933.58
  5371.8 1933.35  5456.3 1937.79    5480 1939.42  5519.4 1940.28  5608.4 1943.16
#Mann= 6 ,-1 , 0
  4369.8     .07       0  4988.1     .07       0  4998.2     .07       0
  5157.2    .035       0  5456.3     .07       0  5519.4    .035       0
Bank Sta=4988.1,4998.2
XS Rating Curve= 0 ,0
Exp/Cntr=0.3,0.1

Type RM Length L Ch R = 1 ,4191    ,264,264,264
BEGIN DESCRIPTION:
Elm 01 22 4190.56
END DESCRIPTION:
XS GIS Cut Line= 3
      1530555.46       6808969.4       1531151.8      6808781.91
      1531745.53      6808432.96
#Sta/Elev= 30
  4377.2 1928.92  4575.9 1927.72  4697.5 1930.36  4775.1 1931.04  4902.4    1931
  4929.5 1930.29  4934.8 1929.05  4974.2 1925.33  4979.7 1923.36  4980.2 1922.86
  4989.3 1922.86  4989.8 1923.36  4994.3 1924.86  4999.6 1925.46  5021.7 1925.61
  5197.5 1924.16  5310.1 1924.56  5319.8 1924.99  5357.6 1926.09  5373.3 1929.28
  5394.7 1932.64  5416.2 1934.66  5459.1 1941.02  5474.8 1942.25  5504.8 1943.39
  5554.9 1942.26    5592  1942.7  5634.9 1942.19  5650.6 1942.81    5691 1942.95
#Mann= 5 ,-1 , 0
  4377.2     .07       0  4979.7     .07       0  4989.8     .07       0
  5310.1    .035       0  5319.8     .07       0
Bank Sta=4979.7,4989.8
XS Rating Curve= 0 ,0
Exp/Cntr=0.3,0.1

Type RM Length L Ch R = 1 ,3927    ,449,449,449
BEGIN DESCRIPTION:
Elm 01 22 3927.43
END DESCRIPTION:
XS GIS Cut Line= 3
       1530604.9      6809156.91      1531326.27      6808953.78
      1531793.59      6808561.76
#Sta/Elev= 30
  4254.5 1928.12  4284.3 1927.42  4421.3 1925.51  4550.5 1928.23  4607.8 1929.24
  4767.1 1929.32  4938.6 1928.74    4961 1928.18  4992.2 1921.95  5014.7 1924.09
  5052.9 1923.46  5169.6 1922.69  5186.6 1921.17  5187.1 1920.67  5196.7 1921.17
  5234.6  1923.5  5263.2  1924.1  5269.8 1925.35  5284.1 1925.97  5319.2 1935.26
  5333.5  1936.6  5341.3 1935.65  5347.8 1937.47  5362.1 1935.85  5368.6 1937.66
  5372.9  1937.8  5397.3 1940.81  5475.3 1943.44  5573.7 1943.18  5613.9  1943.3
#Mann= 12 ,-1 , 0
  4254.5    .035       0  4284.3     .07       0  4550.5    .035       0
  4767.1     .07       0  4938.6    .035       0  5052.9     .07       0
  5052.9    .035       0  5169.6     .07       0  5186.6    .035       0
  5196.7     .07       0  5372.9    .035       0  5573.7     .07       0
Bank Sta=5186.6,5196.7
XS Rating Curve= 0 ,0
Exp/Cntr=0.3,0.1

Type RM Length L Ch R = 1 ,3478    ,524,524,524
BEGIN DESCRIPTION:
Elm 01 22 3478.09
END DESCRIPTION:
XS GIS Cut Line= 3
       1530672.6      6809253.27      1531352.32      6809125.66
      1532013.81      6808737.61
#Sta/Elev= 30
  4015.1 1926.64  4109.1 1924.15  4302.4 1927.34  4510.1 1927.08  4611.3  1927.5
  4713.8 1926.59  4744.6 1924.67  4766.6 1926.34  4788.1 1924.72  4802.6 1925.73
  4825.2    1924    4831 1925.14  4881.8 1923.63  4889.7 1922.31  4899.6 1922.52
  4999.6 1921.19  5007.7 1918.97  5008.2 1918.47  5017.8 1918.97  5065.5 1926.69
  5091.4 1924.72  5115.6 1926.93  5180.2 1928.38  5225.8  1929.3  5348.1 1936.19
  5407.4 1937.35  5423.1 1936.32  5428.9 1937.31  5461.3 1936.81  5473.6 1936.79
#Mann= 11 ,-1 , 0
  4015.1     .07       0  4510.1    .035       0  4611.3     .07       0
  4881.8    .035       0  4899.6     .07       0  5007.7     .07       0
  5017.8     .07       0  5091.4    .035       0  5180.2     .07       0
  5348.1    .035       0  5461.3     .07       0
Bank Sta=5007.7,5017.8
XS Rating Curve= 0 ,0
Exp/Cntr=0.3,0.1

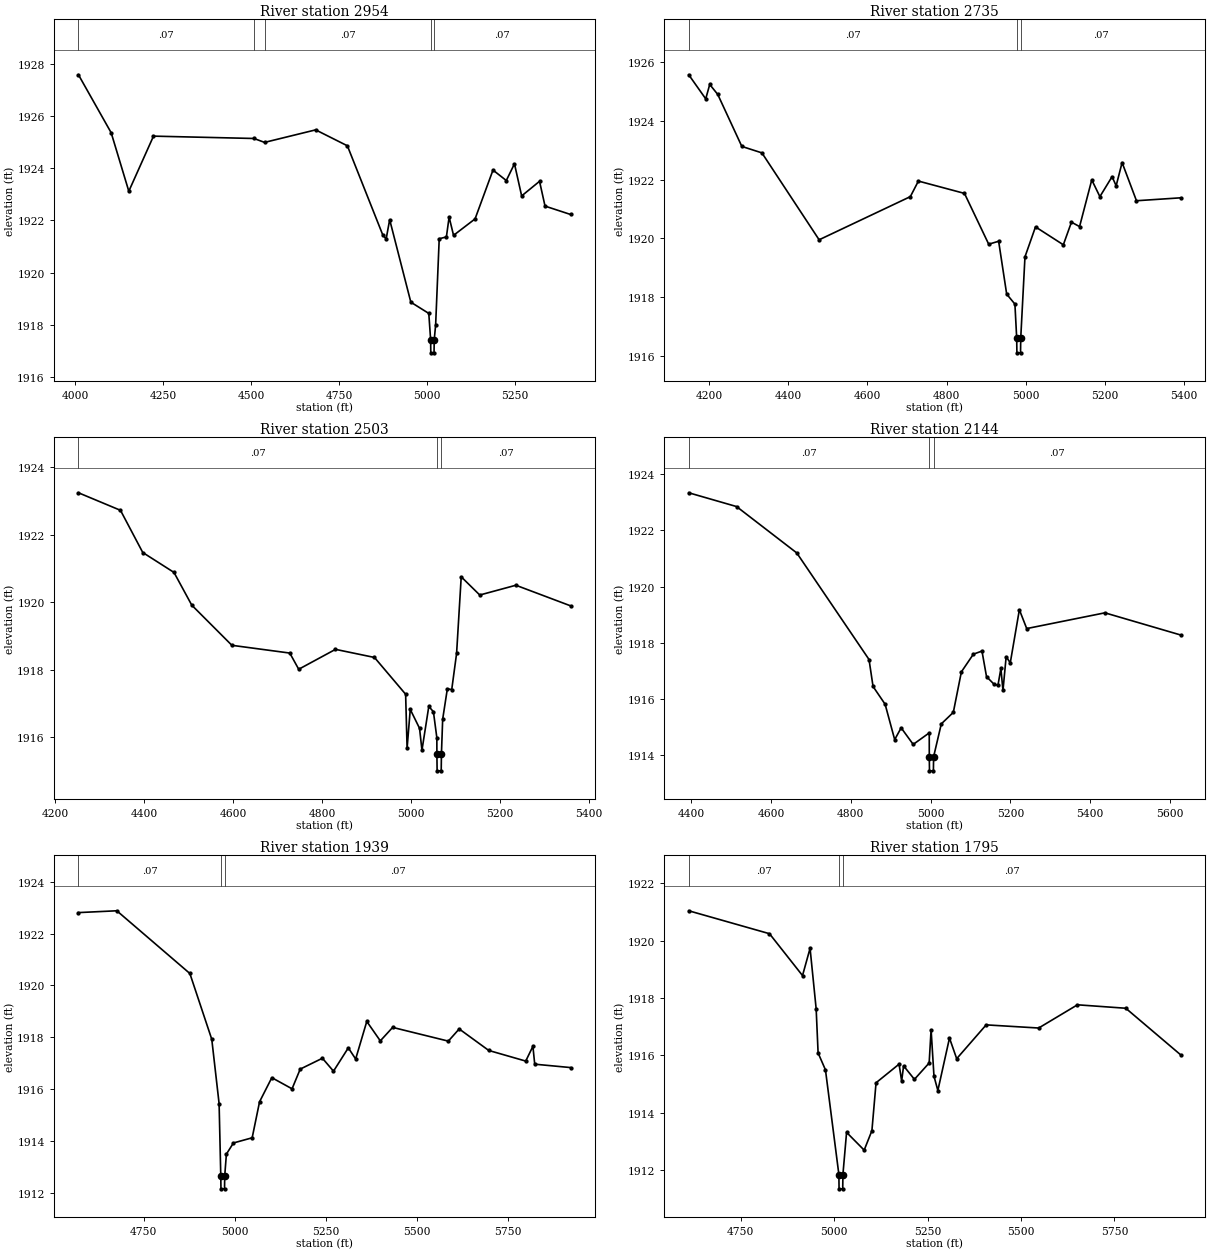
Type RM Length L Ch R = 1 ,2954    ,219,219,219
BEGIN DESCRIPTION:
Elm 01 22 2954.01
END DESCRIPTION:
XS GIS Cut Line= 3
      1530662.18       6809341.8       1531651.8      6809294.93
      1532051.44      6809219.67
#Sta/Elev= 30
  4009.6 1927.58  4102.5 1925.36  4152.6 1923.12  4222.7 1925.23  4508.1 1925.14
  4538.1 1924.99  4683.2 1925.47  4773.3 1924.86  4873.4 1921.46  4883.4 1921.29
  4893.4 1922.03  4953.5 1918.87  5004.5 1918.44  5009.7 1917.43  5010.2 1916.93
  5019.4 1916.93  5019.9 1917.43  5023.9 1917.99  5034.1  1921.3  5054.5 1921.37
  5062.2 1922.13  5074.8 1921.43  5135.9 1922.06  5186.8 1923.93  5224.6 1923.53
  5247.8 1924.17  5268.2 1922.94    5319  1923.5  5334.6 1922.55    5407 1922.23
#Mann= 5 ,-1 , 0
  4009.6     .07       0  4508.1    .035       0  4538.1     .07       0
  5009.7     .07       0  5019.9     .07       0
Bank Sta=5009.7,5019.9
XS Rating Curve= 0 ,0
Exp/Cntr=0.3,0.1

Type RM Length L Ch R = 1 ,2735    ,232,232,232
BEGIN DESCRIPTION:
Elm 01 22 2735.21
END DESCRIPTION:
XS GIS Cut Line= 3
       1530862.7      6809636.08      1531701.27      6809498.05
      1532084.11      6809409.51
#Sta/Elev= 30
  4148.7 1925.57  4191.6 1924.75  4201.7 1925.24    4222  1924.9  4282.8 1923.13
  4333.5 1922.91    4478 1919.95  4708.4 1921.42  4728.7 1921.95  4845.1 1921.53
  4906.3  1919.8  4931.4  1919.9  4951.7  1918.1  4972.5 1917.76    4977  1916.6
  4977.5  1916.1  4986.7  1916.1  4987.2  1916.6  4997.9 1919.37  5024.5 1920.39
  5094.8 1919.78  5115.3 1920.55  5135.8  1920.4  5166.6 1921.99  5187.1 1921.42
  5217.9  1922.1  5228.2 1921.79  5243.2 1922.58  5279.5 1921.28  5391.5 1921.38
#Mann= 3 ,-1 , 0
  4148.7     .07       0    4977     .07       0  4987.2     .07       0
Bank Sta=4977,4987.2
XS Rating Curve= 0 ,0
Exp/Cntr=0.3,0.1

Type RM Length L Ch R = 1 ,2503    ,359,359,359
BEGIN DESCRIPTION:
Elm 01 22 2503.13
END DESCRIPTION:
XS GIS Cut Line= 3
      1531060.63      6809737.64      1531795.02      6809693.36
      1532150.94      6809589.45
#Sta/Elev= 30
  4251.8 1923.24  4346.3 1922.72  4396.4 1921.47  4466.6 1920.88  4506.6 1919.91
  4596.8 1918.72    4727 1918.49  4747.1 1918.01  4829.8  1918.6  4917.4 1918.36
  4987.5 1917.27  4990.8 1915.67  4997.9 1916.82  5018.8 1916.26  5024.2 1915.61
  5039.6 1916.91    5050 1916.75  5057.7 1915.98  5057.8  1915.5  5058.3    1915
  5067.5    1915    5068  1915.5  5070.8 1916.53  5081.3 1917.43  5091.2 1917.41
  5102.1 1918.48  5112.5 1920.75  5154.2 1920.21  5235.4  1920.5  5358.3 1919.89
#Mann= 3 ,-1 , 0
  4251.8     .07       0  5057.8     .07       0    5068     .07       0
Bank Sta=5057.8,5068
XS Rating Curve= 0 ,0
Exp/Cntr=0.3,0.1

Type RM Length L Ch R = 1 ,2144    ,205,205,205
BEGIN DESCRIPTION:
Elm 01 22 2144.11
END DESCRIPTION:
XS GIS Cut Line= 3
      1531065.85      6809807.95      1531792.42      6809886.07
      1532279.42      6809763.67
#Sta/Elev= 30
  4394.1 1923.34  4513.9 1922.85  4664.8  1921.2  4845.8 1917.41  4855.9 1916.45
  4886.1 1915.82  4910.1 1914.56  4926.3 1914.98  4956.5 1914.39  4996.7  1914.8
  4996.8 1913.95  4997.3 1913.45  5007.1 1913.45  5007.6 1913.95  5026.9 1915.12
    5057 1915.53  5077.2 1916.97  5107.3  1917.6  5128.8 1917.71  5140.2  1916.8
  5158.4 1916.54  5168.8 1916.49  5176.2 1917.09  5181.4 1916.31  5189.4 1917.51
  5199.7 1917.29  5222.5 1919.18  5240.9 1918.51  5436.8 1919.07    5627 1918.28
#Mann= 3 ,-1 , 0
  4394.1     .07       0  4996.8     .07       0  5007.6     .07       0
Bank Sta=4996.8,5007.6
XS Rating Curve= 0 ,0
Exp/Cntr=0.3,0.1

Type RM Length L Ch R = 1 ,1939    ,144,144,144
BEGIN DESCRIPTION:
Elm 01 22 1938.848
END DESCRIPTION:
XS GIS Cut Line= 3
      1531079.97        6809963.      1531508.45      6809989.49
      1532416.16      6809836.59
#Sta/Elev= 30
  4570.7 1922.81  4675.9 1922.88  4876.3 1920.46  4936.4 1917.92  4956.5 1915.44
  4961.1 1912.65  4961.6 1912.15  4971.4 1912.15  4971.9 1912.65  4976.5 1913.49
  4995.8 1913.92  5047.2 1914.12  5067.5 1915.51  5101.1 1916.44  5156.6 1916.01
    5179 1916.77  5239.9 1917.19  5270.3 1916.69  5310.9 1917.59  5331.1 1917.16
  5361.6 1918.61  5398.7 1917.86  5432.6 1918.38  5585.3 1917.85  5615.1 1918.32
  5696.2 1917.49  5797.6 1917.08  5817.3 1917.65  5822.3 1916.96  5920.5 1916.83
#Mann= 3 ,-1 , 0
  4570.7     .07       0  4961.1     .07       0  4971.9     .07       0
Bank Sta=4961.1,4971.9
XS Rating Curve= 0 ,0
Exp/Cntr=0.3,0.1

Type RM Length L Ch R = 1 ,1795    ,342,342,342
BEGIN DESCRIPTION:
Elm 01 22 1795.097
END DESCRIPTION:
XS GIS Cut Line= 3
       1531159.6       6810214.2      1531537.76      6810121.76
      1532431.52      6809873.48
#Sta/Elev= 30
  4610.7 1921.04  4826.8 1920.24  4915.2 1918.78  4935.4 1919.73  4951.7 1917.62
  4956.9 1916.08  4976.6 1915.49  5012.5 1911.84    5013 1911.34  5022.8 1911.34
  5023.3 1911.84  5033.1 1913.31  5080.2 1912.69  5100.9 1913.37    5112 1915.04
  5173.6 1915.69  5180.5  1915.1  5185.7 1915.63  5214.7 1915.16  5254.1 1915.73
  5259.3 1916.89    5267 1915.27  5277.4 1914.77  5308.5  1916.6  5327.8 1915.88
  5406.7 1917.06  5547.2 1916.95    5651 1917.76  5780.3 1917.64  5927.6 1916.01
#Mann= 3 ,-1 , 0
  4610.7     .07       0  5012.5     .07       0  5023.3     .07       0
Bank Sta=5012.5,5023.3
XS Rating Curve= 0 ,0
Exp/Cntr=0.3,0.1

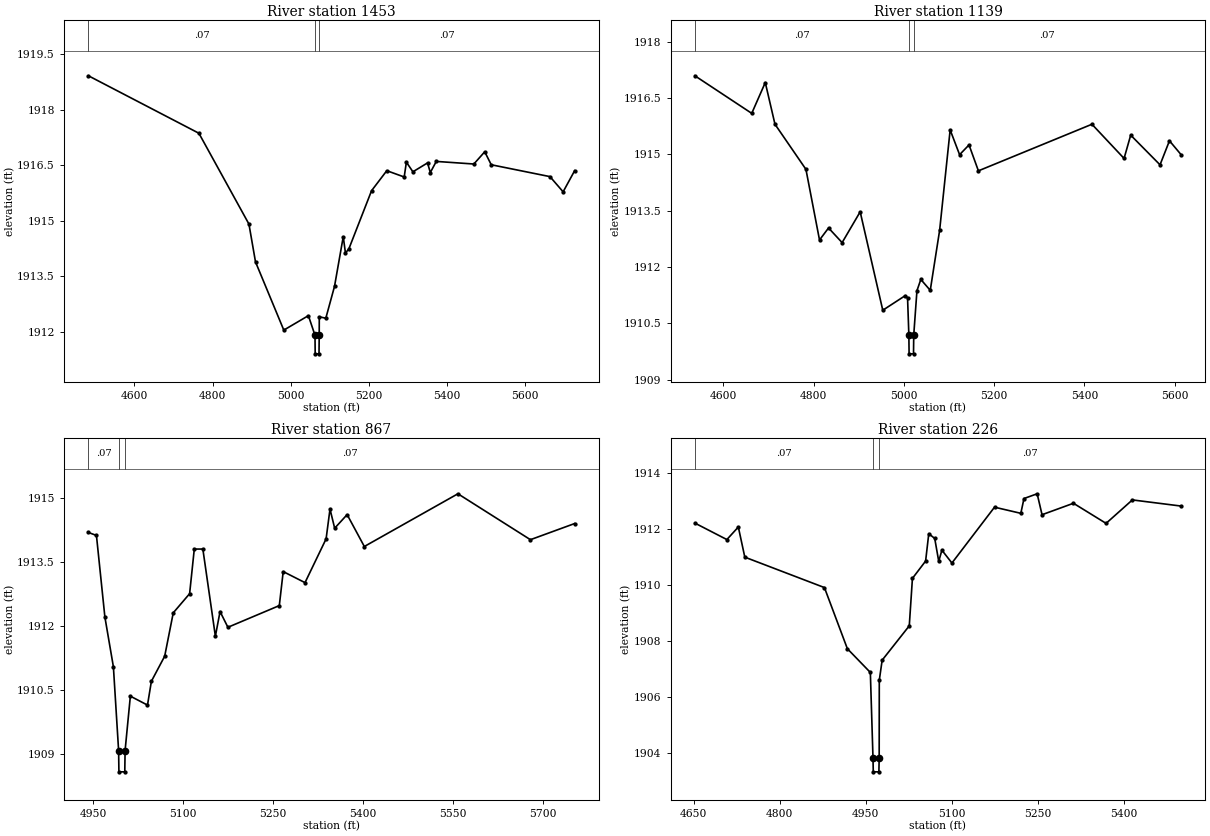
Type RM Length L Ch R = 1 ,1453    ,314,314,314
BEGIN DESCRIPTION:
Elm 01 22 1453.107
END DESCRIPTION:
XS GIS Cut Line= 3
      1531341.86      6810360.04       1531841.8      6810224.84
      1532491.48      6809897.23
#Sta/Elev= 30
  4482.1 1918.91  4765.1 1917.36  4893.3 1914.91  4910.1 1913.89  4982.6 1912.05
  5045.6 1912.44  5062.5 1911.91    5063 1911.41  5072.8 1911.41  5073.3 1911.91
  5073.5 1912.41  5090.2 1912.37  5112.5 1913.23  5134.9 1914.57  5140.5 1914.13
  5149.2 1914.24  5207.4 1915.81  5246.4 1916.35    5291 1916.18  5296.6 1916.58
  5313.3 1916.32  5350.8 1916.56  5357.9  1916.3  5373.2  1916.6  5469.4 1916.53
  5497.3 1916.86    5514 1916.51  5664.4 1916.19  5698.1 1915.78  5727.6 1916.35
#Mann= 3 ,-1 , 0
  4482.1     .07       0  5062.5     .07       0  5073.3     .07       0
Bank Sta=5062.5,5073.3
XS Rating Curve= 0 ,0
Exp/Cntr=0.3,0.1

Type RM Length L Ch R = 1 ,1139    ,272,272,272
BEGIN DESCRIPTION:
Elm 01 22 1139.035
END DESCRIPTION:
XS GIS Cut Line= 3
      1531589.26        6810363.      1532051.89      6810336.35
       1532550.1      6809977.31
#Sta/Elev= 30
  4536.6 1917.09  4662.6 1916.09  4692.6 1916.91  4714.1  1915.8  4782.7  1914.6
  4812.8 1912.72  4832.8 1913.04  4862.9 1912.65  4902.9 1913.47    4953 1910.85
  5002.9 1911.24  5007.9 1911.18  5010.8 1910.19  5011.3 1909.69  5021.1 1909.69
  5021.6 1910.19  5028.7 1911.37  5037.3 1911.67  5058.2 1911.38    5079 1912.98
  5102.3 1915.65  5123.2 1914.99  5144.1 1915.25  5164.9 1914.56  5416.5  1915.8
  5487.7 1914.89  5502.4 1915.51  5567.4 1914.72  5588.3 1915.36  5614.1 1914.99
#Mann= 3 ,-1 , 0
  4536.6     .07       0  5010.8     .07       0  5021.6     .07       0
Bank Sta=5010.8,5021.6
XS Rating Curve= 0 ,0
Exp/Cntr=0.3,0.1

Type RM Length L Ch R = 1 ,867     ,641,641,641
BEGIN DESCRIPTION:
Elm 01 22 866.659
END DESCRIPTION:
XS GIS Cut Line= 3
      1531969.48      6810581.41      1532010.92      6810540.54
      1532589.32      6810057.93
#Sta/Elev= 30
  4941.8  1914.2  4955.2 1914.13  4969.3 1912.21  4983.5 1911.04  4992.2 1909.07
  4992.7 1908.57  5002.5 1908.57    5003 1909.07  5011.8 1910.35  5040.4 1910.14
  5046.9  1910.7  5069.1 1911.29  5083.4 1912.31  5110.7 1912.76  5118.5 1913.81
  5132.8 1913.81  5153.7 1911.76  5161.5 1912.34  5174.6 1911.97  5260.4 1912.48
  5266.9 1913.28  5303.3 1913.02  5338.5 1914.05    5345 1914.75  5352.8  1914.3
  5373.6 1914.62  5402.3 1913.87  5558.5 1915.11  5679.5 1914.03  5753.3 1914.41
#Mann= 3 ,-1 , 0
  4941.8     .07       0  4992.2     .07       0    5003     .07       0
Bank Sta=4992.2,5003
XS Rating Curve= 0 ,0
Exp/Cntr=0.3,0.1

Type RM Length L Ch R = 1 ,226     ,0,0,0
BEGIN DESCRIPTION:
Elm 01 22 225.958
END DESCRIPTION:
XS GIS Cut Line= 3
      1532149.22      6810646.49      1532496.91      6810631.92
      1532706.48      6810177.74
#Sta/Elev= 30
    4652 1912.22  4707.8 1911.63  4727.8 1912.08  4739.1    1911    4878 1909.91
    4918 1907.72  4958.1 1906.87  4962.7 1903.81  4963.2 1903.31    4973 1903.31
  4973.5 1903.81  4973.7 1906.59  4978.7 1907.31    5026 1908.54  5031.5 1910.24
  5054.5 1910.86    5060 1911.84  5070.4 1911.67  5077.4 1910.85  5082.9 1911.25
  5100.4 1910.79  5174.7 1912.79  5220.6 1912.57  5226.1  1913.1  5249.1 1913.27
  5257.6 1912.52  5312.4 1912.93  5369.3 1912.21  5415.2 1913.05  5500.2 1912.83
#Mann= 3 ,-1 , 0
    4652     .07       0  4962.7     .07       0  4973.5     .07       0
Bank Sta=4962.7,4973.5
XS Rating Curve= 0 ,0
Exp/Cntr=0.3,0.1

Chan Stop Cuts=-1
Use User Specified Reach Order=0
Composite Channel Slope=5