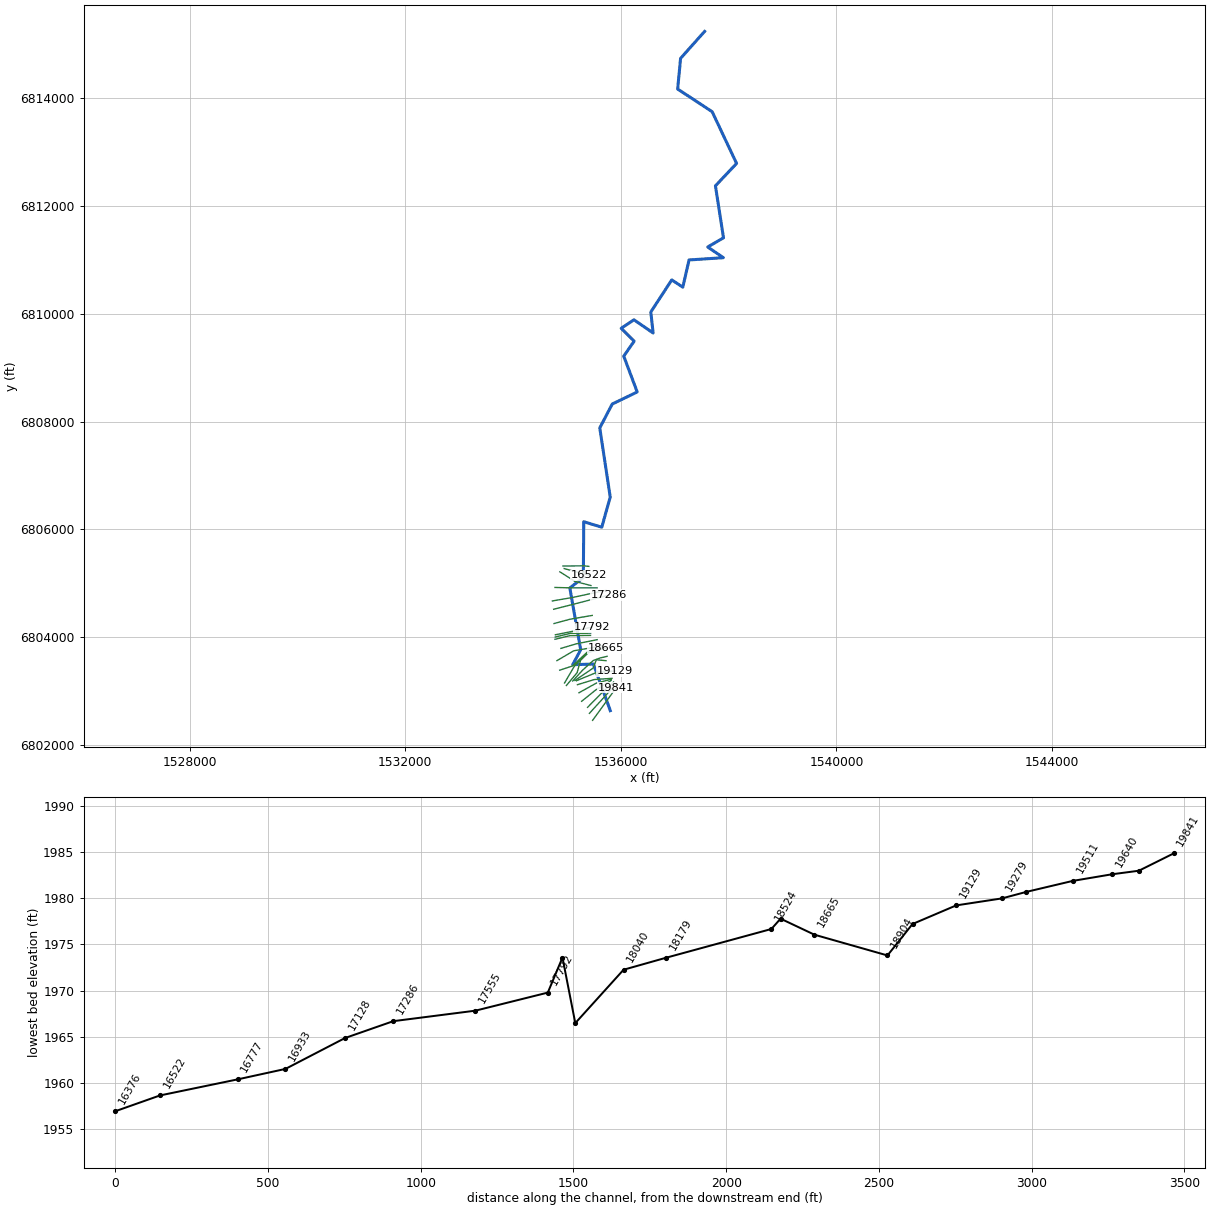
--- Elm 01 24.prj (project) ---

Proj Title=Elm 01 24 Base Level Engineering
Current Plan=p01
Default Exp/Contr=0.3,0.1
English Units
Geom File=g01
Flow File=f01
Plan File=p01
Y Axis Title=Elevation
X Axis Title(PF)=Main Channel Distance
X Axis Title(XS)=Station
BEGIN DESCRIPTION:
Elm 01 24
END DESCRIPTION:
DSS Export Rating Curves= 0
DSS Export Rating Curve Sorted= 0
DSS Export Volume Flow Curves= 0
DXF OffsetX= 0
DXF OffsetY= 0
DXF ScaleX= 1
DXF ScaleY= 10

--- Elm 01 24.p01 (plan) ---

Plan Title=Multiple Run
Program Version=4.10
Short Identifier=Multiple
Geom File=g01
Flow File=f01
Subcritical Flow
K Sum by GR= 0
Std Step Tol= 0.01
Critical Tol= 0.01
Num of Std Step Trials= 20
Max Error Tol= 0.3
Flow Tol Ratio= 0.001
Split Flow NTrial= 30
Split Flow Tol= 0.02
Split Flow Ratio= 0.02
Log Output Level= 0
Friction Slope Method= 1
Unsteady Friction Slope Method= 2
Unsteady Bridges Friction Slope Method= 1
Parabolic Critical Depth
Global Vel Dist= 1 , 1 , 1
Global Log Level= 0
CheckData=True
Encroach Param=-1 ,0,0, 0
BEGIN DESCRIPTION:
Multiple Run
END DESCRIPTION:
Computation Interval=1HOUR
Output Interval=1HOUR
Run HTab= 0
Run UNet= 0
Run PostProcess= 0
Run WQNet= 0
UNET Theta= 1
UNET Theta Warmup= 1
UNET ZTol= 0.02
UNET ZSATol= 0.05
UNET MxIter= 20
UNET MaxInSteps= 0
UNET DtIC= 0
UNET DtMin= 0
UNET MaxCRTS= 20
UNET WFStab= 2
UNET SFStab= 1
UNET WFX= 1
UNET SFX= 1
UNET DSS MLevel= 4
UNET DZMax Abort= 100
UNET Convert EG Bridges= 0
UNET Use Existing IB Tables=-1
UNET Froude Reduction=False
UNET Froude Limit= 1
UNET Froude Power= 10
UNET Time Slicing=0,0, 5
UNET Junction Losses=0
Instantaneous Interval=1HOUR
Write IC File= 0
Write IC File at Sim End=0
Echo Input=False
Echo Parameters=False
Echo Output=False
Write Detailed= 0
WQ AD Non Conservative
WQ ULTIMATE=-1
WQ Max Comp Step=1HOUR
WQ Output Interval=15MIN
WQ Output Selected Increments= 0
WQ Output face flow=0
WQ Output face velocity=0
WQ Output face area=0
WQ Output face dispersion=0
WQ Output cell volume=0
WQ Output cell surface area=0
WQ Output cell continuity=0
WQ Output cumulative cell continuity=0
WQ Output face conc=0
WQ Output face dconc_dx=0
WQ Output face courant=0
WQ Output face peclet=0
WQ Output face adv mass=0
WQ Output face disp mass=0
WQ Output cell mass=0
WQ Output cell source sink temp=0
WQ Output cell source sink nsm=0
WQ Output MaxMinRange=-1
WQ Daily Max Min Mean=-1
WQ Daily Range=0
WQ Daily Time=0
WQ Create Restart=0
WQ Fixed Restart=0
WQ System Summary=0
WQ Use Fixed Temperature=0
Sorting and Armoring Iterations= 10
XS Update Threshold= 0.02
Hydraulics Update Threshold= 0.02
Energy Slope Method= 1
Volume Change Method= 0
XS Weighting Method= 0
Number of US Weighted Cross Sections= 1
Number of DS Weighted Cross Sections= 1
Upstream XS Weight=0.25
Main XS Weight=0.5
Downstream XS Weight=0.25
Number of DS XS's Weighted with US Boundary= 1
Upstream Boundary Weight= 1
Weight of XSs Associated with US Boundary= 0
Number of US XS's Weighted with DS Boundary= 1
Downstream Boundary Weight= 0.5
Weight of XSs Associated with DS Boundary= 0.5
Sediment Output Level= 4
Mass or Volume Output= 0
Output Increment Type= 1
Profile and TS Output Increment= 10
XS Output Flag= 0
XS Output Increment= 10
Disregard all LS=0
Disregard all Conn=0
Disregard all Breaches=0
Disregard all Pumps=0

--- Elm 01 24.f01 (steady flow) ---

Flow Title=Multiple
Number of Profiles=7
Profile Names=10-year,25-year,50-year,1pct_min,100-year,1pct_plu,500-year
River Rch & RM= Elm 01 24,Reach-1,19841
     424     622     796     633    1010    1400    1670
River Rch & RM= Elm 01 24,Reach-1,19727
     540     792    1010     804    1290    1770    2110
River Rch & RM= Elm 01 24,Reach-1,13457
     630     922    1180     927    1490    2040    2410
River Rch & RM= Elm 01 24,Reach-1,6050
     717    1050    1340    1060    1690    2330    2750
Boundary for River Rch & Prof#=Elm 01 24,Reach-1,1
Up Type=0
Dn Type=3
Dn Slope=0.015
Boundary for River Rch & Prof#=Elm 01 24,Reach-1,2
Up Type=0
Dn Type=3
Dn Slope=0.015
Boundary for River Rch & Prof#=Elm 01 24,Reach-1,3
Up Type=0
Dn Type=3
Dn Slope=0.015
Boundary for River Rch & Prof#=Elm 01 24,Reach-1,4
Up Type=0
Dn Type=3
Dn Slope=0.015
Boundary for River Rch & Prof#=Elm 01 24,Reach-1,5
Up Type=0
Dn Type=3
Dn Slope=0.015
Boundary for River Rch & Prof#=Elm 01 24,Reach-1,6
Up Type=0
Dn Type=3
Dn Slope=0.015
Boundary for River Rch & Prof#=Elm 01 24,Reach-1,7
Up Type=0
Dn Type=3
Dn Slope=0.015

--- Elm 01 24.g01 (geometry) ---

Geom Title=Existing Conditions
Program Version=4.10

River Reach=Elm 01 24       ,Reach-1
Reach XY= 30
        1535805.        6802638.      1535491.56      6803501.65
      1535108.12      6803489.16      1535255.47      6803767.84
       1535054.5      6804913.04      1535304.86      6805106.34
      1535312.71       6806141.7      1535646.83      6806040.46
      1535803.78       6806598.5      1535609.77      6807882.39
      1535841.37      6808325.04      1536304.45      6808548.64
      1536054.58        6809213.      1536247.52      6809491.58
      1536007.46      6809729.83      1536244.31      6809887.46
      1536599.41      6809642.73      1536556.62      6810031.96
      1536944.76      6810627.26      1537149.98      6810492.93
      1537265.85      6810997.48      1537901.92      6811039.68
      1537612.07      6811238.01      1537904.98      6811408.19
      1537755.24      6812372.78      1538147.79      6812787.66
      1537694.49      6813747.81       1537054.6      6814167.86
      1537108.74      6814736.44        1537555.        6815238.

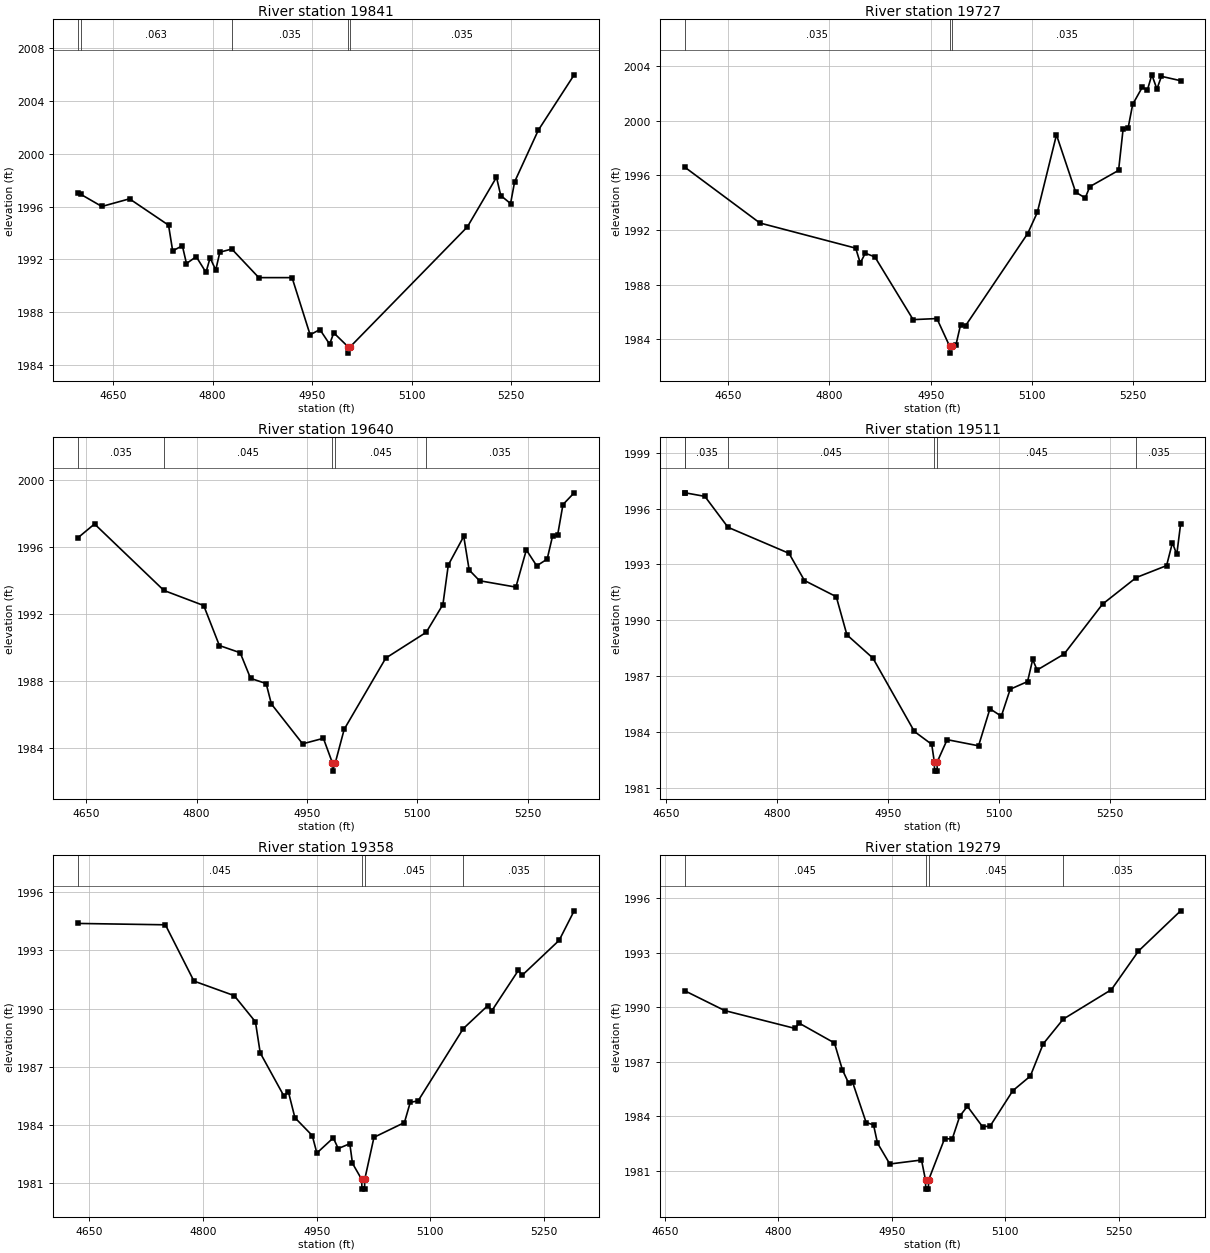
Type RM Length L Ch R = 1 ,19841   ,114,114,114
BEGIN DESCRIPTION:
Elm 01 24 19840.89
END DESCRIPTION:
XS GIS Cut Line= 3
      1535476.89      6802457.26      1535711.26      6802780.17
       1535914.3      6803063.04
#Sta/Elev= 30
  4597.6 1997.04  4601.2 1996.94  4633.2 1996.01  4674.9 1996.59  4733.7 1994.59
  4739.9 1992.64  4754.5 1993.03  4760.7 1991.68  4775.4  1992.2  4790.1 1991.01
  4796.3 1992.11  4804.8 1991.19    4811 1992.54    4829 1992.78  4869.7 1990.61
  4919.8 1990.61    4947 1986.27  4961.7 1986.67  4976.4 1985.56  4982.6 1986.42
  5003.8 1985.38  5004.1 1984.88  5007.8 1985.38  5183.9 1994.46  5227.8 1998.23
  5234.2 1996.84    5249 1996.23  5255.1 1997.88  5290.7 2001.79  5344.8    2006
#Mann= 5 ,-1 , 0
  4597.6    .035       0  4601.2    .063       0    4829    .035       0
  5003.8    .035       0  5007.8    .035       0
Bank Sta=5003.8,5007.8
XS Rating Curve= 0 ,0
Exp/Cntr=0.3,0.1

Type RM Length L Ch R = 1 ,19727   ,87,87,87
BEGIN DESCRIPTION:
Elm 01 24 19726.67
END DESCRIPTION:
XS GIS Cut Line= 3
      1535417.85      6802587.46      1535702.58      6802899.96
      1535910.71      6803132.18
#Sta/Elev= 30
  4585.6 1996.61    4697 1992.52  4838.9 1990.68  4845.7 1989.59  4853.1 1990.31
  4867.3 1990.04    4924 1985.45  4959.2 1985.53  4978.1  1983.5  4978.4    1983
  4982.1  1983.5  4987.5 1983.62  4994.3 1985.08  5001.7 1985.01  5093.7 1991.75
  5107.9 1993.29  5136.3 1998.97  5164.7 1994.78  5178.9 1994.35  5185.7 1995.18
  5228.3 1996.37    5235 1999.39  5242.5 1999.49  5249.2  2001.2  5263.4 2002.45
  5270.9 2002.24  5277.6 2003.36  5285.1 2002.32  5291.8 2003.25  5320.2 2002.93
#Mann= 3 ,-1 , 0
  4585.6    .035       0  4978.1    .035       0  4982.1    .035       0
Bank Sta=4978.1,4982.1
XS Rating Curve= 0 ,0
Exp/Cntr=0.3,0.1

Type RM Length L Ch R = 1 ,19640   ,129,129,129
BEGIN DESCRIPTION:
Elm 01 24 19640.25
END DESCRIPTION:
XS GIS Cut Line= 3
       1535383.1      6802698.54      1535640.08      6802958.99
      1535865.76      6803169.05
#Sta/Elev= 30
  4639.1 1996.57  4661.3 1997.38  4755.6 1993.41  4809.7 1992.51    4831 1990.12
  4859.3 1989.69  4873.4 1988.16  4894.6 1987.85  4901.7 1986.63  4944.2 1984.25
  4972.4 1984.58  4984.6 1983.12  4984.8 1982.62  4988.6 1983.12  5000.7 1985.12
  5057.2 1989.37  5112.2 1990.91  5134.9 1992.57  5142.2 1994.93  5163.2 1996.64
  5170.6 1994.63  5184.7 1993.99  5234.1 1993.61  5248.3 1995.83  5262.4 1994.88
  5276.6 1995.28  5283.9 1996.65  5290.8 1996.71  5298.1 1998.54  5313.3 1999.24
#Mann= 5 ,-1 , 0
  4639.1    .035       0  4755.6    .045       0  4984.6    .045       0
  4988.6    .045       0  5112.2    .035       0
Bank Sta=4984.6,4988.6
XS Rating Curve= 0 ,0
Exp/Cntr=0.3,0.1

Type RM Length L Ch R = 1 ,19511   ,153,153,153
BEGIN DESCRIPTION:
Elm 01 24 19511.22
END DESCRIPTION:
XS GIS Cut Line= 3
      1535273.75      6802811.42       1535530.7      6803018.02
      1535821.15      6803197.82
#Sta/Elev= 30
  4674.9 1996.84  4675.6 1996.85  4702.2 1996.66  4733.5    1995  4816.1  1993.6
    4837 1992.14  4880.1 1991.27  4894.5 1989.22  4929.7 1987.97  4985.8 1984.03
  5009.3 1983.34  5012.8  1982.4  5013.1  1981.9  5016.6  1981.9  5016.8  1982.4
  5030.2 1983.59  5072.7 1983.26  5088.1 1985.25  5103.5 1984.85  5115.5  1986.3
    5139 1986.71    5146  1987.9  5151.9 1987.33  5188.5 1988.19  5240.5 1990.87
  5286.2  1992.3  5327.2 1992.94  5335.1 1994.17    5341 1993.54  5346.2 1995.18
#Mann= 6 ,-1 , 0
  4674.9    .045       0  4675.6    .035       0  4733.5    .045       0
  5012.8    .045       0  5016.8    .045       0  5286.2    .035       0
Bank Sta=5012.8,5016.8
XS Rating Curve= 0 ,0
Exp/Cntr=0.3,0.1

Type RM Length L Ch R = 1 ,19358   ,79,79,79
BEGIN DESCRIPTION:
Elm 01 24 19358.23
END DESCRIPTION:
XS GIS Cut Line= 3
      1535225.11      6802969.38      1535542.85      6803146.49
      1535824.14      6803221.15
#Sta/Elev= 30
  4635.1 1994.39  4750.2 1994.32  4787.9 1991.42  4841.1 1990.67  4869.1 1989.32
  4875.4 1987.72  4906.8 1985.49  4912.5 1985.73  4921.2 1984.38  4944.1 1983.46
  4950.2 1982.56  4971.9 1983.34  4978.4 1982.79  4993.7 1983.04  4997.2 1982.03
  5009.4  1981.2  5009.7  1980.7  5013.2  1980.7  5013.4  1981.2  5025.6 1983.37
  5065.8 1984.13  5073.5 1985.17  5083.9 1985.25  5143.5 1988.97    5176 1990.16
  5181.2 1989.89  5216.2 1991.97  5221.3 1991.72  5270.1 1993.52  5289.9 1995.04
#Mann= 4 ,-1 , 0
  4635.1    .045       0  5009.4    .045       0  5013.4    .045       0
  5143.5    .035       0
Bank Sta=5009.4,5013.4
XS Rating Curve= 0 ,0
Exp/Cntr=0.3,0.1

Type RM Length L Ch R = 1 ,19279   ,150,150,150
BEGIN DESCRIPTION:
Elm 01 24 19278.7
END DESCRIPTION:
XS GIS Cut Line= 3
      1535195.61       6803118.7      1535508.13       6803214.2
      1535836.27      6803236.77
#Sta/Elev= 30
  4676.3  1990.9  4729.2 1989.81  4822.1 1988.83  4827.6 1989.12  4874.3 1988.03
  4884.8 1986.56  4893.2 1985.81  4898.4 1985.86  4916.2 1983.66    4926 1983.53
  4931.2 1982.53  4947.5 1981.38  4989.4  1981.6  4994.7  1980.5    4995    1980
  4998.5    1980  4998.8  1980.5    5020 1982.78    5030 1982.75    5040 1984.01
  5050.1 1984.55  5070.1 1983.43  5080.1 1983.46  5110.2 1985.41  5133.3 1986.21
  5150.3 1987.98  5176.8 1989.34  5240.5 1990.96  5276.3 1993.08    5332 1995.29
#Mann= 4 ,-1 , 0
  4676.3    .045       0  4994.7    .045       0  4998.8    .045       0
  5176.8    .035       0
Bank Sta=4994.7,4998.8
XS Rating Curve= 0 ,0
Exp/Cntr=0.3,0.1

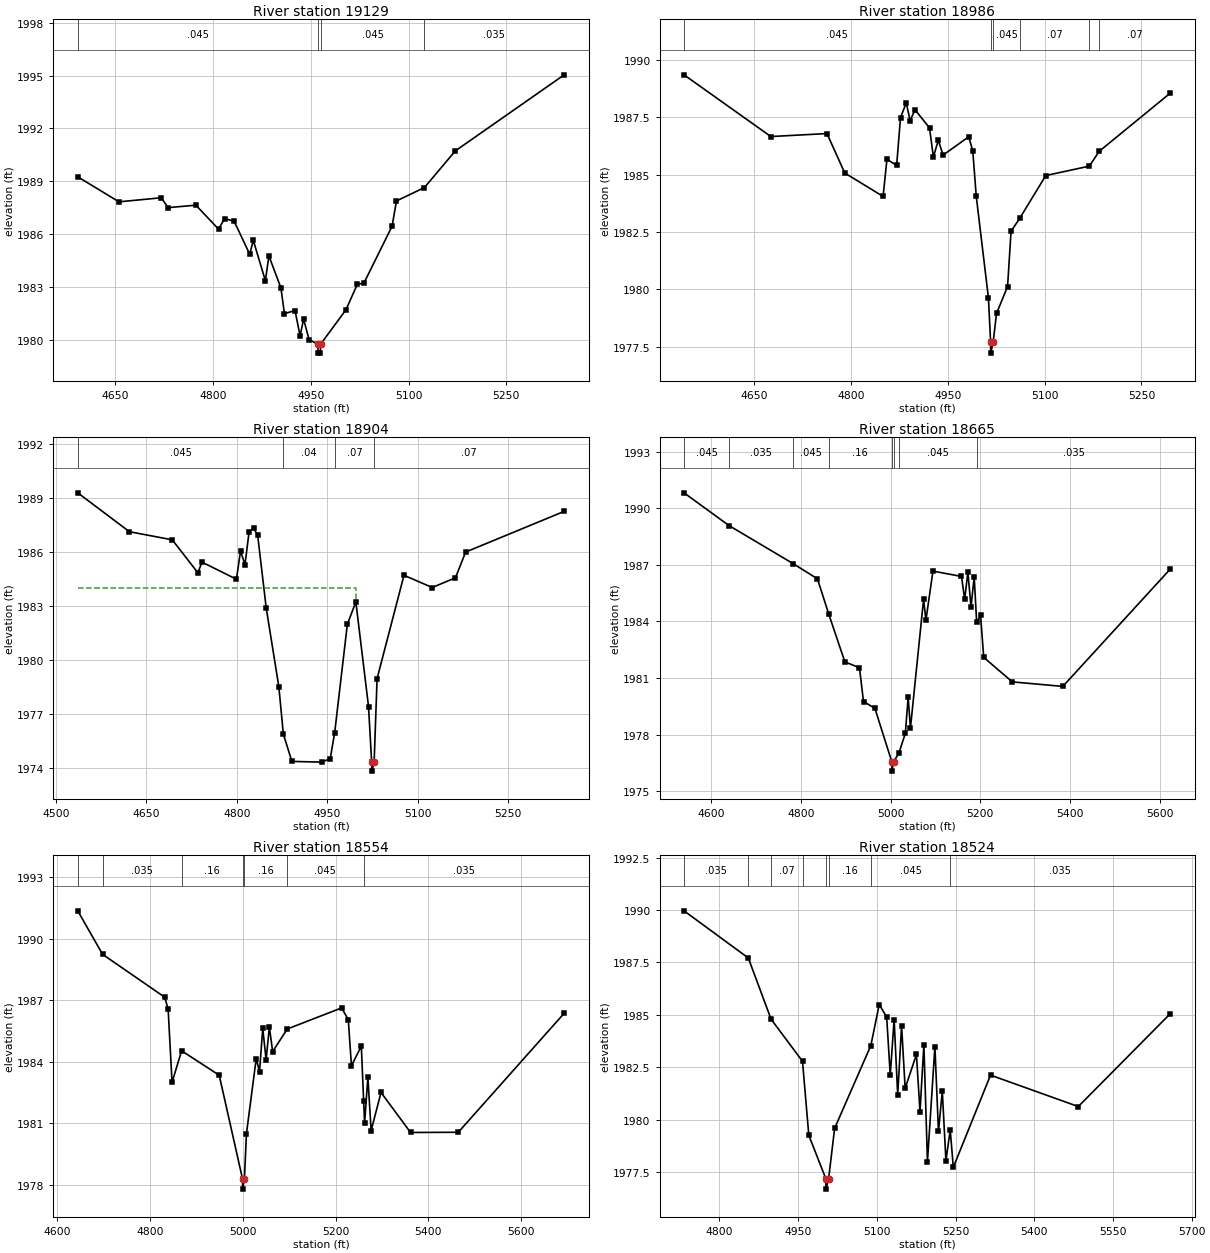
Type RM Length L Ch R = 1 ,19129   ,143,143,143
BEGIN DESCRIPTION:
Elm 01 24 19128.71
END DESCRIPTION:
XS GIS Cut Line= 3
       1535176.5      6803192.27      1535555.01      6803347.88
      1535891.79      6803372.06
#Sta/Elev= 30
  4592.1 1989.25  4655.4 1987.83  4720.2 1988.06    4731  1987.5  4773.5 1987.64
  4808.3 1986.28  4817.5 1986.88  4832.2 1986.73  4856.2 1984.85  4861.6 1985.65
  4880.2 1983.35  4885.6 1984.76    4904 1982.95  4909.5 1981.48  4925.7 1981.66
  4933.5 1980.22  4938.9 1981.17  4947.3 1980.01  4960.8 1979.74  4961.1 1979.24
  4964.6 1979.24  4964.9 1979.74  5003.9  1981.7  5021.4 1983.15  5031.4 1983.21
  5074.7 1986.44  5081.5 1987.88  5124.4 1988.64  5171.8 1990.72    5339 1995.04
#Mann= 4 ,-1 , 0
  4592.1    .045       0  4960.8    .045       0  4964.9    .045       0
  5124.4    .035       0
Bank Sta=4960.8,4964.9
XS Rating Curve= 0 ,0
Exp/Cntr=0.3,0.1

Type RM Length L Ch R = 1 ,18986   ,82,82,82
BEGIN DESCRIPTION:
Elm 01 24 18986.31
END DESCRIPTION:
XS GIS Cut Line= 4
      1535148.78      6803197.46      1535483.83      6803424.27
      1535546.72      6803581.51      1535725.31      6803563.95
#Sta/Elev= 30
  4541.6 1989.35  4676.1 1986.66    4763 1986.79  4790.6 1985.07  4849.9 1984.05
  4855.9 1985.67  4870.9  1985.4  4876.9 1987.48  4885.8 1988.13  4891.8 1987.35
  4899.3 1987.83  4921.8 1987.04  4927.8 1985.77  4935.5  1986.5  4942.8 1985.85
  4982.5 1986.65  4988.8 1986.04  4994.2 1984.06  5013.1 1979.62  5016.4 1977.72
  5016.6 1977.22  5020.5 1977.72  5025.6 1978.95  5042.7 1980.12  5048.1 1982.53
  5062.1 1983.12  5101.9 1984.96  5169.3 1985.37  5184.8 1986.02    5295 1988.56
#Mann= 6 ,-1 , 0
  4541.6    .045       0  5016.4     .07       0  5020.5    .045       0
  5062.1     .07       0  5169.3    .045       0  5184.8     .07       0
Bank Sta=5016.4,5020.5
XS Rating Curve= 0 ,0
Exp/Cntr=0.3,0.1

Type RM Length L Ch R = 1 ,18904   ,239,239,239
BEGIN DESCRIPTION:
Elm 01 24 18871.11
END DESCRIPTION:
XS GIS Cut Line= 5
       1535108.4      6803187.85      1535296.33      6803393.02
      1535488.59       6803567.3      1535613.95      6803613.87
       1535745.4      6803644.82
#Sta/Elev= 30
  4536.3 1989.27    4622 1987.11    4693 1986.66  4735.5 1984.83  4742.3 1985.42
  4799.4 1984.47  4806.2 1986.04  4813.6 1985.28  4820.4 1987.11  4827.8 1987.31
  4834.6 1986.91  4848.8 1982.87  4869.7  1978.5  4877.2 1975.87  4891.3 1974.35
  4940.7 1974.31  4954.9  1974.5  4962.3 1975.95  4983.3 1981.97  4997.4 1983.21
  5018.4  1977.4  5023.6 1974.31  5023.9 1973.81  5027.7 1974.31  5032.6 1978.95
  5077.2 1984.69    5124 1984.01  5162.5 1984.55  5179.4 1985.98  5342.8 1988.24
#Mann= 4 ,-1 , 0
  4536.3    .045       0  4877.2     .04       0  4962.3     .07       0
  5027.7     .07       0
#XS Ineff= 2 , 0
       0  4997.4    1984               0
Permanent Ineff=
       F       F
Bank Sta=5023.6,5027.7
XS Rating Curve= 0 ,0
Exp/Cntr=0.3,0.1

Type RM Length L Ch R = 1 ,18665   ,111,111,111
BEGIN DESCRIPTION:
Elm 01 24 12.0
END DESCRIPTION:
XS GIS Cut Line= 5
      1534990.41      6803103.52      1535189.82      6803342.24
      1535252.49      6803570.26      1535404.61      6803720.79
      1535718.16      6803796.52
#Sta/Elev= 30
  4539.7 1990.81  4640.3 1989.07  4783.4 1987.05  4837.1 1986.25  4862.4 1984.37
  4898.2 1981.85  4930.7 1981.54  4939.7 1979.75  4965.1 1979.39  5002.7 1976.56
  5002.9 1976.06  5006.8 1976.56  5018.5 1977.01    5033 1978.07  5039.2 1979.98
  5044.3 1978.34  5073.6 1985.17  5078.8 1984.06  5094.5 1986.66  5158.1 1986.38
  5165.2 1985.16  5172.3 1986.61  5179.3 1984.77  5186.4 1986.35  5191.9 1983.94
  5200.6 1984.31  5207.6 1982.09  5271.3 1980.79  5383.9 1980.55  5623.8 1986.78
#Mann= 8 ,-1 , 0
  4539.7    .045       0  4640.3    .035       0  4783.4    .045       0
  4862.4     .16       0  5002.7     .07       0  5006.8     .16       0
  5018.5    .045       0  5191.9    .035       0
Bank Sta=5002.7,5006.8
XS Rating Curve= 0 ,0
Exp/Cntr=0.3,0.1

Type RM Length L Ch R = 1 ,18554   ,30,30,30
BEGIN DESCRIPTION:
Elm 01 24 18554.38
END DESCRIPTION:
XS GIS Cut Line= 5
      1534956.05      6803149.97      1535140.08       6803464.2
      1535292.85      6803620.45      1535399.52      6803724.49
       1535706.9      6803797.89
#Sta/Elev= 30
  4644.8 1991.36  4698.3 1989.24  4832.2 1987.15  4839.5 1986.57  4847.9    1983
  4868.5 1984.54  4949.5 1983.35  4999.7  1978.3    5000  1977.8  5003.8  1978.3
  5008.2 1980.51  5029.2 1984.16  5036.3 1983.52  5043.3 1985.63  5050.5  1984.1
  5057.5  1985.7  5064.6  1984.5  5095.9  1985.6  5213.1 1986.63  5227.5 1986.06
  5234.3 1983.81  5255.6 1984.77  5260.6 1982.08  5262.6 1981.01  5269.7 1983.24
  5276.7 1980.65    5298 1982.51  5361.6 1980.56  5464.4 1980.57  5692.5 1986.37
#Mann= 7 ,-1 , 0
  4644.8    .045       0  4698.3    .035       0  4868.5     .16       0
  4999.7     .07       0  5003.8     .16       0  5095.9    .045       0
  5260.6    .035       0
Bank Sta=4999.7,5003.8
XS Rating Curve= 0 ,0
Exp/Cntr=0.3,0.1

Type RM Length L Ch R = 1 ,18524   ,345,345,345
BEGIN DESCRIPTION:
Elm 01 24 10.0
END DESCRIPTION:
XS GIS Cut Line= 5
      1534866.58      6803387.73      1535099.99      6803464.73
      1535338.35      6803686.56      1535396.65      6803740.27
      1535666.79      6803798.42
#Sta/Elev= 30
  4732.6 1989.96  4855.1 1987.71  4898.5 1984.79  4958.4 1982.78  4970.4 1979.25
  5002.8 1977.18  5003.2 1976.68  5008.2 1977.18  5019.6 1979.58  5088.6 1983.53
  5104.6 1985.49  5118.8 1984.89  5125.6 1982.13    5133 1984.77  5139.8 1981.17
  5147.2 1984.48    5154 1981.49  5175.5 1983.11  5182.3 1980.38  5189.7 1983.57
  5196.5 1977.99  5210.7 1983.48  5217.5 1979.43  5224.8 1981.36  5231.7 1978.04
  5239.9  1979.5  5245.8 1977.72  5316.7 1982.12  5483.9 1980.62  5659.6 1985.06
#Mann= 8 ,-1 , 0
  4732.6    .035       0  4855.1     .16       0  4898.5     .07       0
  4958.4     .16       0  5002.8     .07       0  5008.2     .16       0
  5088.6    .045       0  5239.9    .035       0
Bank Sta=5002.8,5008.2
XS Rating Curve= 0 ,0
Exp/Cntr=0.3,0.1

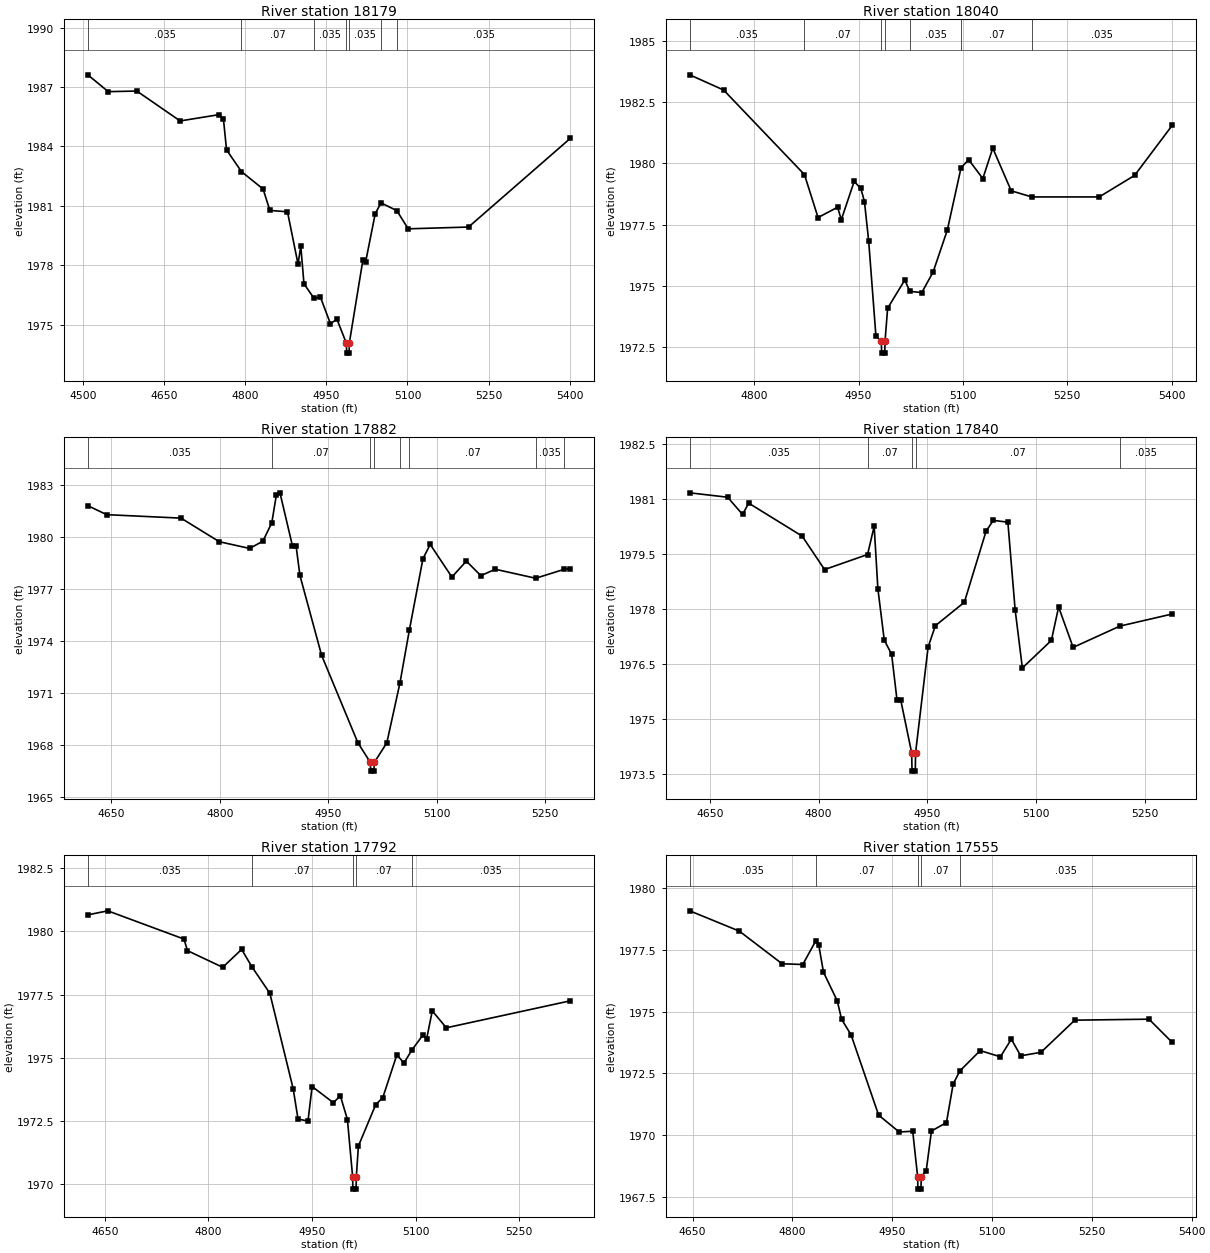
Type RM Length L Ch R = 1 ,18179   ,139,139,139
BEGIN DESCRIPTION:
Elm 01 24 18299.45
END DESCRIPTION:
XS GIS Cut Line= 3
      1534815.47      6803564.92      1535126.34      6803747.51
      1535650.47      6803837.31
#Sta/Elev= 30
  4508.8 1987.62  4546.7 1986.77  4599.5  1986.8  4679.6 1985.29  4751.8 1985.61
  4759.6  1985.4  4765.4 1983.83    4793 1982.73    4833 1981.85  4845.5 1980.77
  4878.1  1980.7  4897.6 1978.06  4902.7 1978.96  4908.6 1977.06  4927.2 1976.33
    4939 1976.39  4957.6 1975.04  4969.4 1975.28    4987 1974.06  4987.5 1973.56
    4992 1973.56  4992.4 1974.06  5017.7 1978.29  5022.7 1978.18  5040.4 1980.61
  5051.1 1981.15  5080.3 1980.76  5101.3 1979.84  5212.9 1979.93  5401.1 1984.41
#Mann= 7 ,-1 , 0
  4508.8    .035       0    4793     .07       0  4927.2    .035       0
    4987    .035       0  4992.4    .035       0  5051.1     .07       0
  5080.3    .035       0
Bank Sta=4987,4992.4
XS Rating Curve= 0 ,0
Exp/Cntr=0.3,0.1

Type RM Length L Ch R = 1 ,18040   ,158,158,158
BEGIN DESCRIPTION:
Elm 01 24 18039.91
END DESCRIPTION:
XS GIS Cut Line= 3
       1534888.3      6803792.31      1535171.33      6803875.66
      1535561.95      6803953.78
#Sta/Elev= 30
  4707.3 1983.61    4756 1982.99  4872.2 1979.54  4891.7 1977.79  4919.8 1978.21
  4925.1  1977.7  4943.6 1979.26  4953.2 1978.98  4958.4 1978.44  4964.5 1976.82
  4974.9 1972.95  4982.6 1972.76  4983.1 1972.26  4987.6 1972.26    4988 1972.76
  4991.7 1974.09  5016.3 1975.24  5023.7 1974.78  5040.8 1974.73  5057.1 1975.57
  5077.5 1977.28  5097.2 1979.82  5108.1 1980.15  5128.5 1979.38  5142.8 1980.62
  5169.3 1978.88  5198.9 1978.63  5295.7 1978.63  5346.7 1979.51  5400.7 1981.55
#Mann= 7 ,-1 , 0
  4707.3    .035       0  4872.2     .07       0  4982.6     .07       0
    4988     .07       0  5023.7    .035       0  5097.2     .07       0
  5198.9    .035       0
Bank Sta=4982.6,4988
XS Rating Curve= 0 ,0
Exp/Cntr=0.3,0.1

Type RM Length L Ch R = 1 ,17882   ,42,42,42
BEGIN DESCRIPTION:
Elm 01 24 8.0
END DESCRIPTION:
XS GIS Cut Line= 3
      1534779.61      6803961.44      1535059.63      6804028.67
      1535438.73      6804032.91
#Sta/Elev= 30
  4617.5 1981.79  4643.6 1981.27  4746.4 1981.07  4799.3 1979.71  4841.2 1979.32
  4859.6 1979.74  4871.9  1980.8  4878.1 1982.38  4883.2 1982.53  4900.5 1979.46
  4905.5 1979.46  4910.8 1977.76  4940.8 1973.15  4990.9 1968.11  5008.2 1966.97
  5008.6 1966.47  5013.1 1966.47  5013.6 1966.97  5030.9  1968.1  5049.1 1971.56
    5062 1974.59  5080.9 1978.73  5090.9 1979.55  5120.9 1977.67  5140.9 1978.59
  5160.9 1977.75  5180.9 1978.12  5236.7  1977.6  5276.5 1978.12  5284.6 1978.16
#Mann= 8 ,-1 , 0
  4617.5    .035       0  4871.9     .07       0  5008.2     .07       0
  5013.6     .07       0  5049.1    .035       0    5062     .07       0
  5236.7    .035       0  5276.5     .07       0
Bank Sta=5008.2,5013.6
XS Rating Curve= 0 ,0
Exp/Cntr=0.3,0.1

Type RM Length L Ch R = 1 ,17840   ,48,48,48
BEGIN DESCRIPTION:
Elm 01 24 7.0
END DESCRIPTION:
XS GIS Cut Line= 3
      1534784.16      6804003.24      1535064.14      6804070.47
      1535441.67      6804074.69
#Sta/Elev= 30
  4622.2 1981.16  4674.5 1981.04  4695.1 1980.57  4703.5 1980.88  4777.3 1979.98
  4808.2 1979.07  4867.5 1979.48  4876.6 1980.25  4881.7 1978.55  4890.5 1977.15
  4900.7 1976.76    4908 1975.53  4913.1 1975.53  4928.3 1974.08  4928.8 1973.58
  4933.3 1973.58  4933.7 1974.08    4951 1976.96    4961 1977.54    5001 1978.18
    5031 1980.12    5041 1980.41    5061 1980.36    5071 1977.98    5081 1976.39
    5121 1977.14    5131 1978.05    5151 1976.95  5215.5 1977.53  5287.7 1977.86
#Mann= 5 ,-1 , 0
  4622.2    .035       0  4867.5     .07       0  4928.3     .07       0
  4933.7     .07       0  5215.5    .035       0
Bank Sta=4928.3,4933.7
XS Rating Curve= 0 ,0
Exp/Cntr=0.3,0.1

Type RM Length L Ch R = 1 ,17792   ,237,237,237
BEGIN DESCRIPTION:
Elm 01 24 17710.91
END DESCRIPTION:
XS GIS Cut Line= 3
      1534786.65      6804045.05      1535099.16      6804107.56
      1535470.38      6804187.35
#Sta/Elev= 30
  4625.4 1980.66  4654.3 1980.82  4764.6  1979.7  4769.7 1979.24  4820.7 1978.58
  4848.1 1979.29  4862.7 1978.61  4888.9 1977.55  4922.7 1973.76  4929.7 1972.56
  4944.1 1972.48  4950.1 1973.85  4980.8 1973.21    4991 1973.48  5001.2 1972.54
  5008.7 1970.28  5009.1 1969.78  5013.7 1969.78  5014.1 1970.28  5017.1 1971.49
  5042.1 1973.13  5052.4 1973.41  5072.8 1975.11    5083 1974.78  5094.3 1975.29
  5110.7  1975.9  5115.8 1975.73    5124 1976.85  5144.4 1976.18  5323.8 1977.25
#Mann= 5 ,-1 , 0
  4625.4    .035       0  4862.7     .07       0  5008.7     .07       0
  5014.1     .07       0  5094.3    .035       0
Bank Sta=5008.7,5014.1
XS Rating Curve= 0 ,0
Exp/Cntr=0.3,0.1

Type RM Length L Ch R = 1 ,17555   ,269,269,269
BEGIN DESCRIPTION:
Elm 01 24 17454.77
END DESCRIPTION:
XS GIS Cut Line= 3
      1534761.07      6804252.65      1535054.52      6804332.52
      1535469.43       6804403.7
#Sta/Elev= 30
  4645.7 1979.07  4720.2 1978.25  4784.5 1976.93  4815.6  1976.9    4835 1977.85
  4839.5  1977.7  4846.7 1976.59  4867.4 1975.43    4874 1974.68  4888.1 1974.06
  4929.6 1970.81  4960.5 1970.13  4980.8 1970.16  4988.2 1968.32  4988.6 1967.82
  4993.2 1967.82  4993.6 1968.32    5001 1968.55    5009 1970.17  5031.5 1970.51
  5041.6 1972.07  5051.7  1972.6  5082.2 1973.42  5112.6 1973.17    5129 1973.88
  5143.1 1973.21  5173.5 1973.35  5224.3 1974.65  5335.9 1974.69  5370.8 1973.75
#Mann= 5 ,-1 , 0
  4645.7    .035       0    4835     .07       0  4988.2     .07       0
  4993.6     .07       0  5051.7    .035       0
Bank Sta=4988.2,4993.6
XS Rating Curve= 0 ,0
Exp/Cntr=0.3,0.1

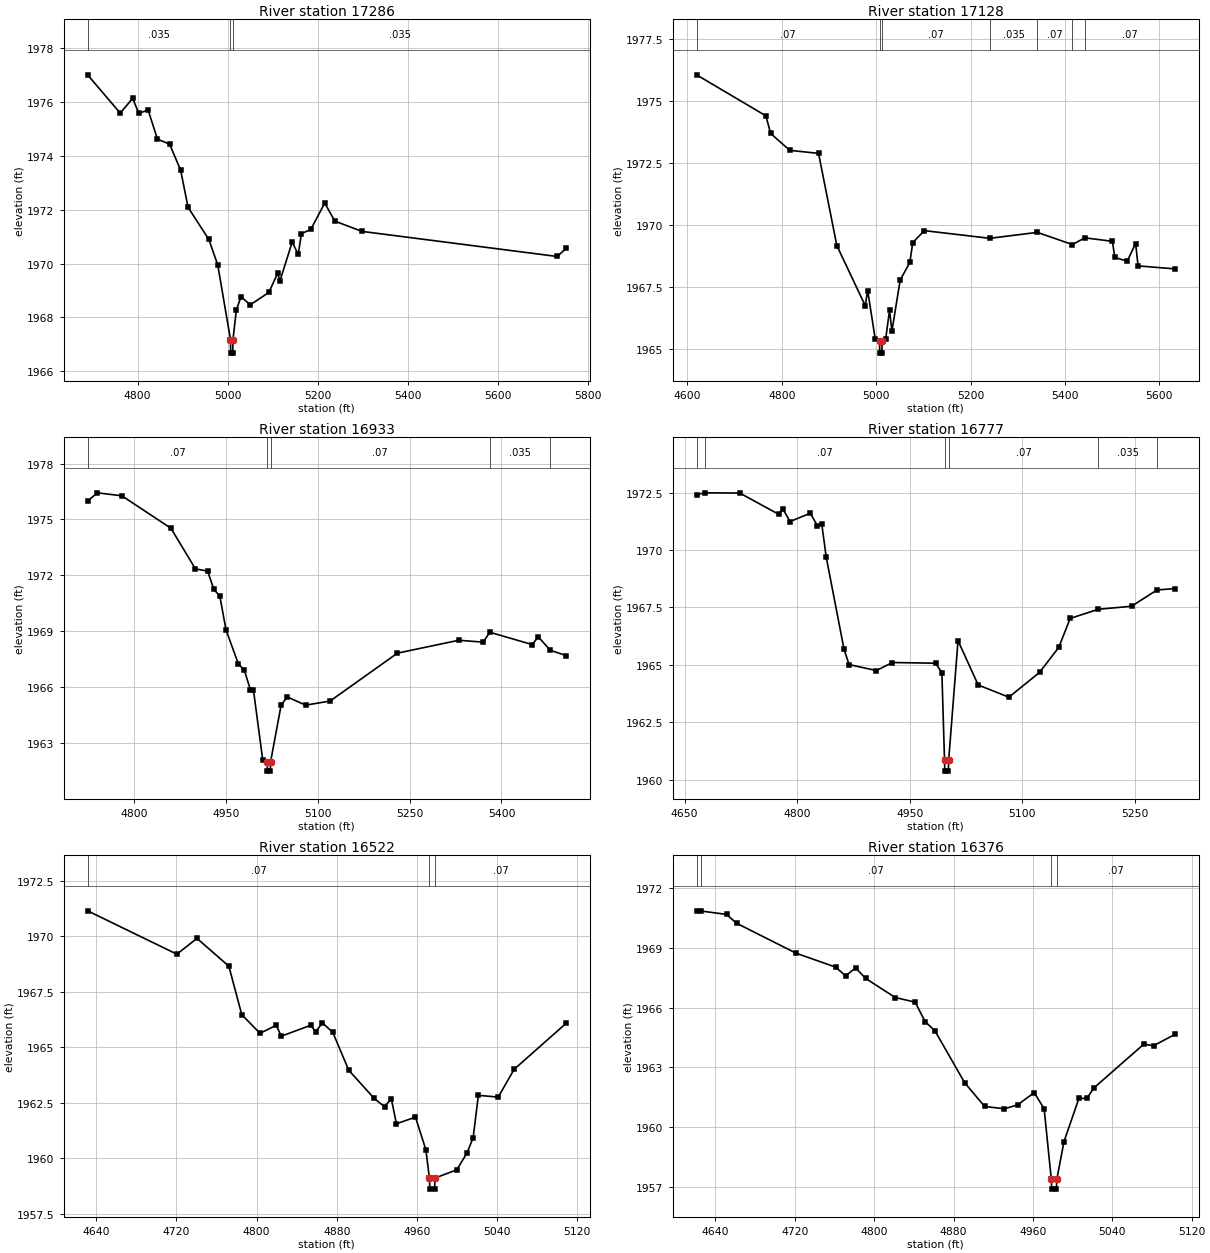
Type RM Length L Ch R = 1 ,17286   ,158,158,158
BEGIN DESCRIPTION:
Elm 01 24 17285.8
END DESCRIPTION:
XS GIS Cut Line= 3
      1534754.67      6804518.02      1535056.74      6804594.41
       1535784.2      6804782.24
#Sta/Elev= 30
  4689.1 1976.99  4761.6 1975.57  4789.2 1976.12  4802.9 1975.56  4823.5 1975.69
  4844.2 1974.61  4871.3 1974.42  4895.7 1973.46  4912.3 1972.08  4958.5 1970.89
  4978.3 1969.94  5006.5 1967.18  5006.9 1966.68  5011.5 1966.68    5012 1967.18
  5019.5 1968.28  5029.9 1968.77  5050.5 1968.47  5091.8 1968.93  5111.2 1969.64
  5116.4 1969.36  5143.5 1970.79    5157 1970.34  5164.1 1971.11  5184.8 1971.26
  5215.8 1972.24  5238.3 1971.57  5298.4 1971.19  5732.2 1970.26    5752 1970.56
#Mann= 3 ,-1 , 0
  4689.1    .035       0  5006.5    .035       0    5012    .035       0
Bank Sta=5006.5,5012
XS Rating Curve= 0 ,0
Exp/Cntr=0.3,0.1

Type RM Length L Ch R = 1 ,17128   ,195,195,195
BEGIN DESCRIPTION:
Elm 01 24 17127.89
END DESCRIPTION:
XS GIS Cut Line= 3
      1534730.39      6804672.54      1535107.09      6804736.77
      1535724.31      6804870.12
#Sta/Elev= 30
  4619.7 1976.05  4766.4  1974.4  4776.5 1973.69  4817.1 1973.01    4878 1972.89
  4916.7 1969.18  4976.9 1966.76    4982 1967.37  4998.2  1965.4  5007.2 1965.35
  5007.6 1964.85  5012.2 1964.85  5012.7 1965.35  5020.2 1965.42  5028.3 1966.57
  5033.4 1965.74  5050.9 1967.79  5071.3  1968.5  5077.6  1969.3    5102 1969.78
  5240.7 1969.47  5341.3 1969.71  5415.7 1969.22    5442 1969.49  5500.4 1969.35
  5505.5  1968.7  5531.7 1968.55  5549.6 1969.26  5554.8 1968.36  5633.3 1968.24
#Mann= 7 ,-1 , 0
  4619.7     .07       0  5007.2     .07       0  5012.7     .07       0
  5240.7    .035       0  5341.3     .07       0  5415.7    .035       0
    5442     .07       0
Bank Sta=5007.2,5012.7
XS Rating Curve= 0 ,0
Exp/Cntr=0.3,0.1

Type RM Length L Ch R = 1 ,16933   ,156,156,156
BEGIN DESCRIPTION:
Elm 01 24 16933.69
END DESCRIPTION:
XS GIS Cut Line= 3
      1534778.99      6804922.53       1535049.8      6804915.59
       1535560.5       6804915.2
#Sta/Elev= 30
    4724 1975.99    4740 1976.43    4780 1976.27  4860.1 1974.53  4900.1 1972.35
  4920.1 1972.23  4930.1 1971.26  4940.1 1970.87  4950.1 1969.07  4970.1 1967.27
  4980.1  1966.9    4990 1965.85  4994.9 1965.85  5010.1 1962.09  5017.4    1962
  5017.8  1961.5  5022.5  1961.5  5022.9    1962  5040.1 1965.04  5050.1 1965.48
  5080.1 1965.04  5120.1 1965.26  5230.1 1967.83  5330.1 1968.52  5370.1 1968.42
    5381 1968.95  5450.1 1968.29  5460.1  1968.7    5480 1967.98  5505.6  1967.7
#Mann= 5 ,-1 , 0
    4724     .07       0  5017.4     .07       0  5022.9     .07       0
    5381    .035       0    5480     .07       0
Bank Sta=5017.4,5022.9
XS Rating Curve= 0 ,0
Exp/Cntr=0.3,0.1

Type RM Length L Ch R = 1 ,16777   ,255,255,255
BEGIN DESCRIPTION:
Elm 01 24 16777.38
END DESCRIPTION:
XS GIS Cut Line= 3
      1534869.28      6805212.44      1535150.49      6805033.64
      1535445.18      6804958.32
#Sta/Elev= 30
    4666 1972.41  4676.7 1972.49  4723.5 1972.48  4775.1 1971.56  4781.1 1971.78
  4790.4 1971.24  4817.5  1971.6  4826.8 1971.06  4832.7 1971.13  4838.7 1969.68
  4862.4 1965.67  4869.1 1965.01  4905.6 1964.75  4926.7  1965.1  4984.3 1965.07
  4992.7 1964.66  4996.2 1960.87  4996.6 1960.37  5001.3 1960.37  5001.8 1960.87
  5014.2 1966.05  5041.1 1964.12    5082 1963.59  5122.8 1964.67  5148.4 1965.76
  5163.6 1967.02  5201.2 1967.42  5245.3 1967.55  5279.3 1968.26  5303.4 1968.32
#Mann= 6 ,-1 , 0
    4666    .035       0  4676.7     .07       0  4996.2     .07       0
  5001.8     .07       0  5201.2    .035       0  5279.3     .07       0
Bank Sta=4996.2,5001.8
XS Rating Curve= 0 ,0
Exp/Cntr=0.3,0.1

Type RM Length L Ch R = 1 ,16522   ,146,146,146
BEGIN DESCRIPTION:
Elm 01 24 16526.85
END DESCRIPTION:
XS GIS Cut Line= 3
      1534949.11      6805273.22      1535200.84      6805203.78
      1535410.69      6805150.29
#Sta/Elev= 30
  4631.3 1971.14  4720.4 1969.19  4740.5  1969.9  4772.3 1968.65  4785.2 1966.47
  4803.4 1965.63  4819.6 1965.99  4824.7  1965.5  4853.9 1965.99  4859.1  1965.7
  4865.6  1966.1    4876 1965.68    4892 1963.97  4917.4  1962.7  4927.7 1962.33
  4934.5 1962.69  4939.6 1961.56  4958.6 1961.86    4969 1960.39  4972.5 1959.12
    4973 1958.62  4977.7 1958.62  4978.1 1959.12  4999.9 1959.49  5010.2 1960.26
  5016.2 1960.94  5021.4 1962.84  5041.2 1962.76  5057.1 1964.01    5109 1966.08
#Mann= 3 ,-1 , 0
  4631.3     .07       0  4972.5     .07       0  4978.1     .07       0
Bank Sta=4972.5,4978.1
XS Rating Curve= 0 ,0
Exp/Cntr=0.3,0.1

Type RM Length L Ch R = 1 ,16376   ,151,151,151
BEGIN DESCRIPTION:
Elm 01 24 16375.92
END DESCRIPTION:
XS GIS Cut Line= 3
      1534924.84       6805320.1      1535310.22      6805323.57
      1535406.54      6805313.92
#Sta/Elev= 30
  4621.1 1970.84  4625.6 1970.83  4651.3 1970.66  4661.3 1970.22  4721.3 1968.72
  4761.3 1968.02  4771.3 1967.58  4781.3 1967.99  4791.3 1967.46  4821.3  1966.5
  4841.3 1966.27  4851.3  1965.3  4861.3 1964.83  4891.3 1962.23  4911.3 1961.05
  4931.3 1960.93  4944.6 1961.13  4961.3 1961.74  4971.3 1960.93  4978.5 1957.41
  4978.9 1956.91  4983.6 1956.91  4984.1 1957.41  4991.3 1959.29  5006.4 1961.46
  5014.3 1961.45  5021.3 1961.97  5071.6 1964.16  5081.6 1964.09  5103.3 1964.66
#Mann= 4 ,-1 , 0
  4621.1    .035       0  4625.6     .07       0  4978.5     .07       0
  4984.1     .07       0
Bank Sta=4978.5,4984.1
XS Rating Curve= 0 ,0
Exp/Cntr=0.3,0.1