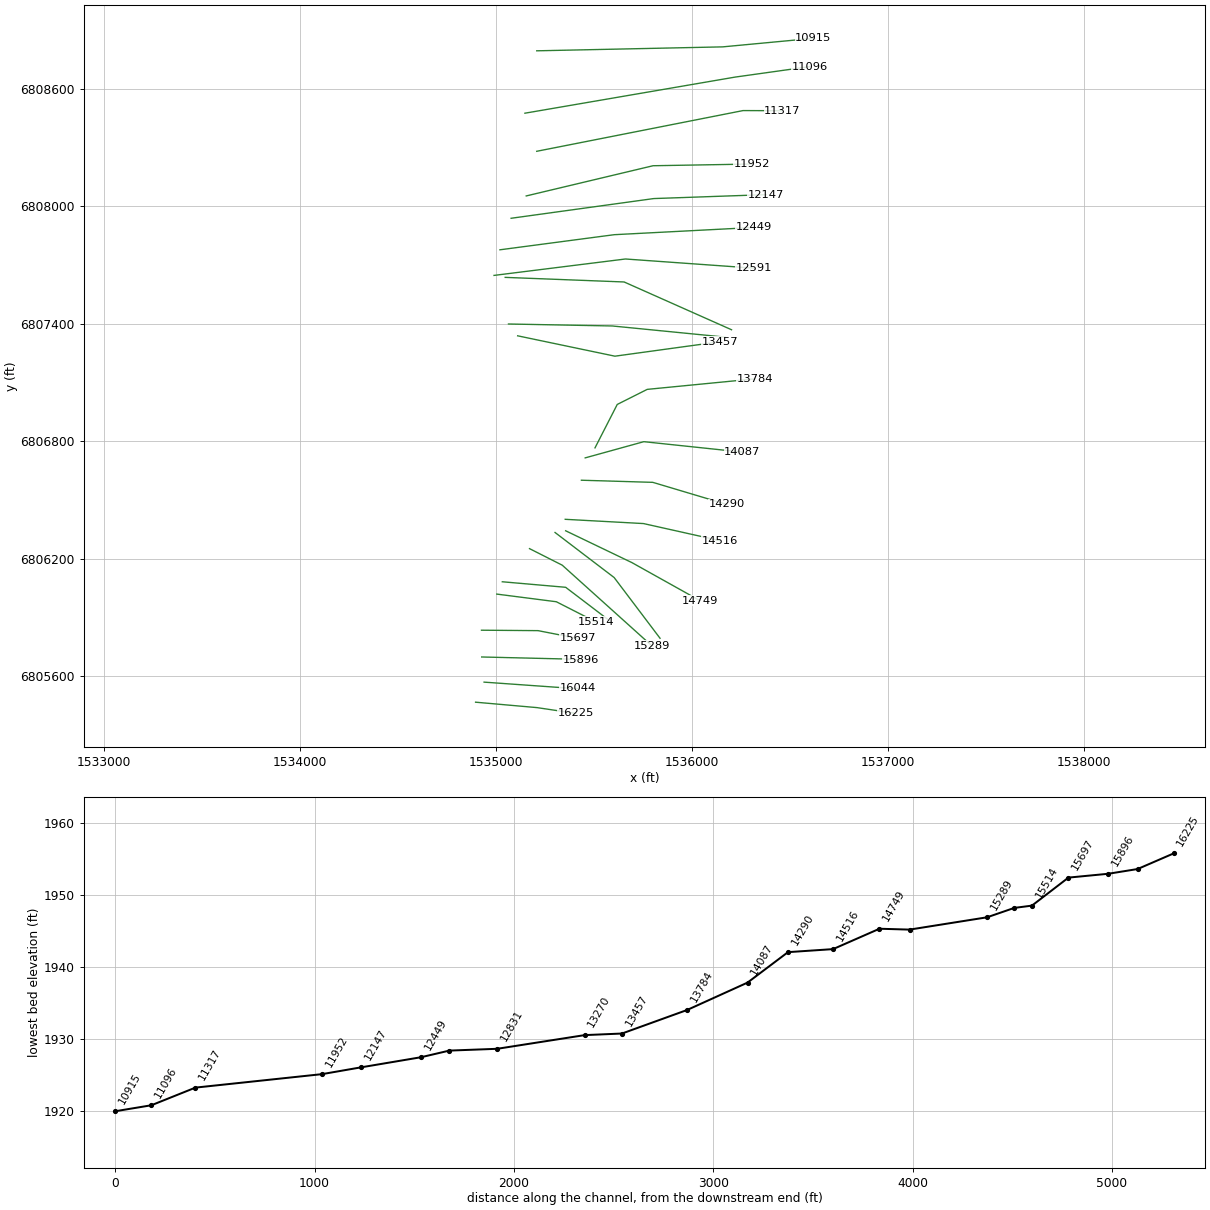
HEC-RAS study Elm 01 24.prj: Elm 01 24 Base Level Engineering

--- Elm 01 24.g01 (geometry) --- (continued)

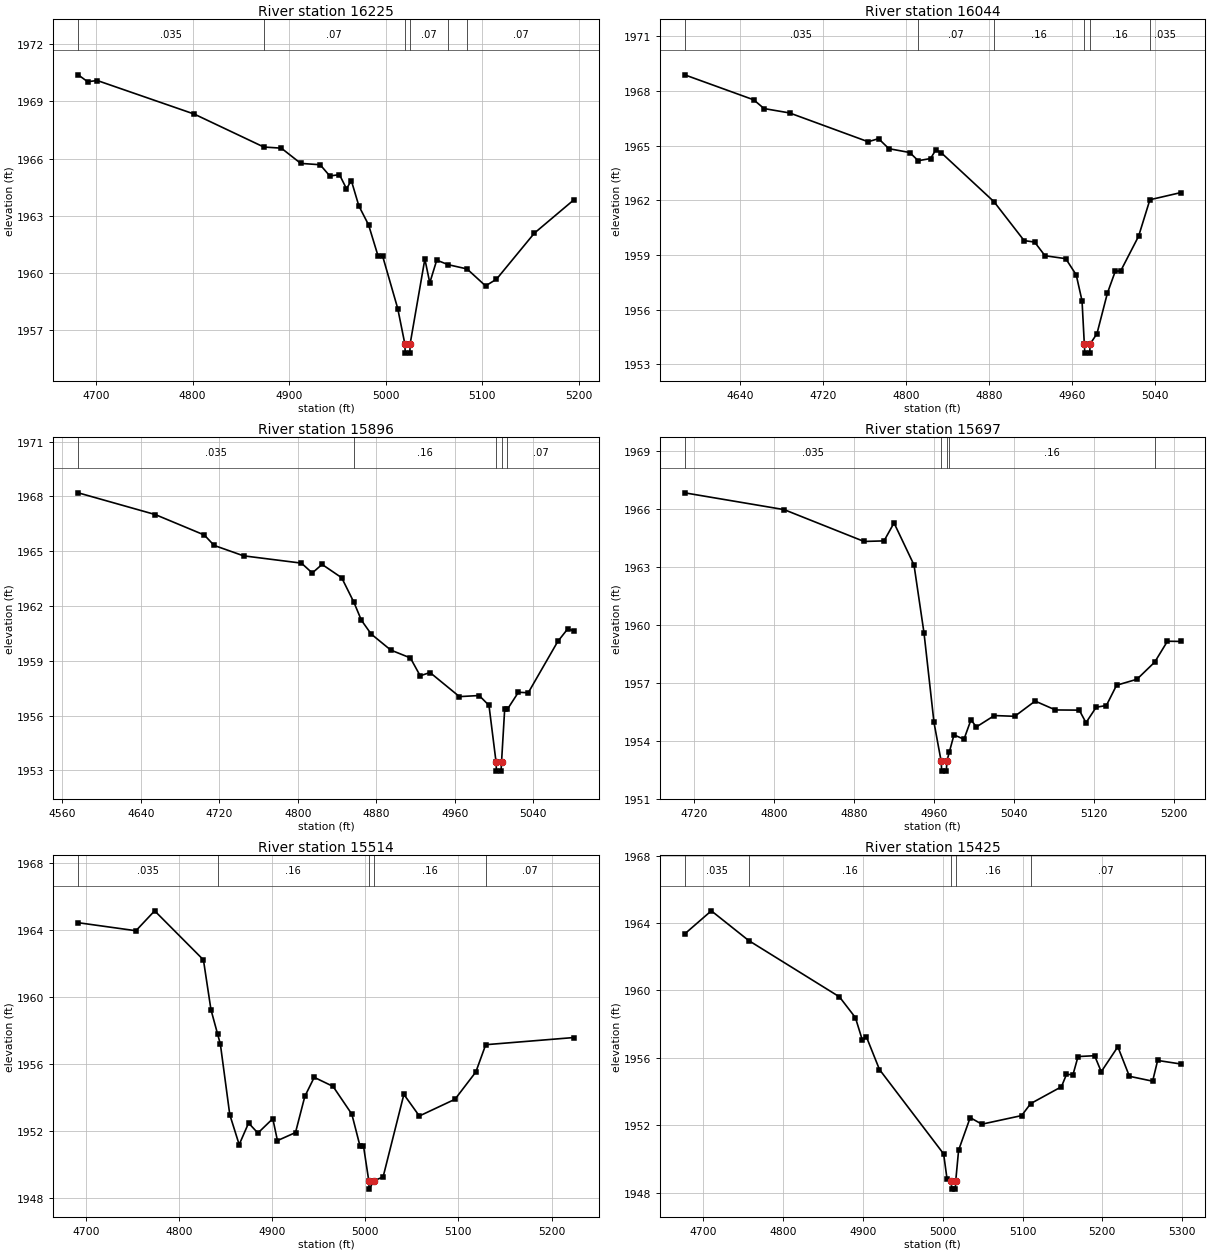
Type RM Length L Ch R = 1 ,16225   ,181,181,181
BEGIN DESCRIPTION:
Elm 01 24 16225.17
END DESCRIPTION:
XS GIS Cut Line= 3
       1534895.3      6805467.67      1535209.52      6805439.89
       1535405.8      6805410.53
#Sta/Elev= 30
  4681.4  1970.4  4691.1 1970.04  4701.2  1970.1  4801.6 1968.34  4873.7 1966.61
  4891.9 1966.55    4912 1965.75  4932.1 1965.68  4942.1 1965.09  4952.1 1965.16
  4959.4 1964.42  4964.4 1964.85  4972.2 1963.52  4982.3 1962.52  4992.1 1960.89
  4996.8 1960.89  5012.5 1958.13  5019.8 1956.29  5020.3 1955.79    5025 1955.79
  5025.4 1956.29  5040.6 1960.73  5045.7 1959.48  5052.9 1960.67    5065 1960.43
  5084.3 1960.21  5103.5 1959.32  5114.8 1959.67  5154.1 1962.09  5195.3 1963.85
#Mann= 6 ,-1 , 0
  4681.4    .035       0  4873.7     .07       0  5019.8     .07       0
  5025.4     .07       0    5065     .16       0  5084.3     .07       0
Bank Sta=5019.8,5025.4
XS Rating Curve= 0 ,0
Exp/Cntr=0.3,0.1

Type RM Length L Ch R = 1 ,16044   ,148,148,148
BEGIN DESCRIPTION:
Elm 01 24 16044.25
END DESCRIPTION:
XS GIS Cut Line= 3
      1534938.67       6805570.1      1535355.35      6805540.59
      1535415.45      6805537.62
#Sta/Elev= 30
  4586.9 1968.88  4653.4 1967.51  4663.4 1967.03    4688 1966.79  4763.7 1965.21
  4773.7 1965.38  4783.7 1964.83  4803.8 1964.62  4811.9 1964.17  4823.8 1964.29
  4828.9 1964.76  4833.9 1964.62    4885 1961.92    4914 1959.79  4924.1 1959.71
  4934.1 1958.96  4954.1  1958.8  4964.2 1957.91  4969.8 1956.49    4972 1954.12
  4972.5 1953.62  4977.2 1953.62  4977.6 1954.12  4984.2 1954.69  4994.2  1956.9
  5001.9 1958.12    5007 1958.12  5024.3 1960.03  5035.2 1962.03  5064.8 1962.42
#Mann= 6 ,-1 , 0
  4586.9    .035       0  4811.9     .07       0    4885     .16       0
    4972     .07       0  4977.6     .16       0  5035.2    .035       0
Bank Sta=4972,4977.6
XS Rating Curve= 0 ,0
Exp/Cntr=0.3,0.1

Type RM Length L Ch R = 1 ,15896   ,199,199,199
BEGIN DESCRIPTION:
Elm 01 24 15895.67
END DESCRIPTION:
XS GIS Cut Line= 3
      1534926.57      6805698.57      1535362.09      6805688.09
      1535431.69      6805683.56
#Sta/Elev= 30
  4576.2  1968.2  4654.7 1967.01  4704.7 1965.89  4714.7 1965.32  4744.7 1964.75
  4803.7 1964.35  4814.7 1963.81  4824.7 1964.28  4844.7 1963.55  4857.2  1962.2
  4864.7 1961.23  4874.7 1960.47  4894.7 1959.59  4914.7 1959.16  4924.7 1958.18
  4934.7 1958.36  4964.7 1957.04  4984.8  1957.1  4994.8 1956.56    5002 1953.46
  5002.4 1952.96  5007.1 1952.96  5007.6 1953.46  5010.8 1956.35  5013.6 1956.35
  5024.8 1957.28  5034.8 1957.25  5064.9 1960.06  5074.9 1960.74  5081.6 1960.64
#Mann= 5 ,-1 , 0
  4576.2    .035       0  4857.2     .16       0    5002     .07       0
  5007.6     .16       0  5013.6     .07       0
Bank Sta=5002,5007.6
XS Rating Curve= 0 ,0
Exp/Cntr=0.3,0.1

Type RM Length L Ch R = 1 ,15697   ,183,183,183
BEGIN DESCRIPTION:
Elm 01 24 15697.14
END DESCRIPTION:
XS GIS Cut Line= 3
       1534925.5      6805835.29      1535214.08      6805833.12
      1535417.92      6805793.19
#Sta/Elev= 30
  4710.3 1966.85  4809.8 1965.98  4889.8 1964.33  4909.8 1964.36  4919.8 1965.29
  4939.8 1963.11  4949.8 1959.59  4959.8 1954.95    4967 1952.93  4967.5 1952.43
  4972.2 1952.43  4972.6 1952.93  4975.2 1953.43  4979.8 1954.31  4989.8 1954.08
  4996.8 1955.09  5002.2 1954.72  5020.2 1955.31  5040.6 1955.27    5061 1956.06
  5081.3  1955.6  5105.2 1955.59  5111.9 1954.94  5122.1 1955.74  5132.3 1955.83
  5142.5 1956.88  5162.9 1957.19  5180.7 1958.08  5193.4 1959.16  5206.6 1959.15
#Mann= 5 ,-1 , 0
  4710.3    .035       0    4967     .07       0  4972.6    .035       0
  4975.2     .16       0  5180.7     .07       0
Bank Sta=4967,4972.6
XS Rating Curve= 0 ,0
Exp/Cntr=0.3,0.1

Type RM Length L Ch R = 1 ,15514   ,89,89,89
BEGIN DESCRIPTION:
Elm 01 24 15514.39
END DESCRIPTION:
XS GIS Cut Line= 3
      1535003.54      6806019.76      1535307.39      6805980.69
      1535509.08      6805877.95
#Sta/Elev= 30
  4691.6 1964.46  4753.6 1963.98  4773.7 1965.17  4826.1 1962.24  4834.2 1959.26
  4841.3 1957.81  4844.3  1957.2  4854.4 1952.99  4864.5  1951.2  4874.6 1952.49
  4884.6 1951.89  4900.6 1952.75  4905.6 1951.44    4925 1951.92    4935 1954.08
  4945.1 1955.22  4965.3 1954.68  4985.5 1953.02  4994.2 1951.13    4998 1951.13
  5003.7 1949.04  5004.1 1948.54  5009.3 1949.04  5019.1 1949.27  5041.4  1954.2
    5058 1952.91  5096.3 1953.91  5118.7 1955.54  5129.3 1957.17  5224.3  1957.6
#Mann= 5 ,-1 , 0
  4691.6    .035       0  4841.3     .16       0  5003.7     .07       0
  5009.3     .16       0  5129.3     .07       0
Bank Sta=5003.7,5009.3
XS Rating Curve= 0 ,0
Exp/Cntr=0.3,0.1

Type RM Length L Ch R = 1 ,15425   ,136,136,136
BEGIN DESCRIPTION:
Elm 01 24 15424.57
END DESCRIPTION:
XS GIS Cut Line= 3
      1535031.77      6806082.69      1535355.14      6806054.48
      1535591.49      6805874.46
#Sta/Elev= 30
  4676.5 1963.35  4709.9 1964.72  4756.7 1962.96  4870.5 1959.62  4890.5 1958.39
  4899.3 1957.04  4904.3 1957.25  4920.7 1955.31  5001.1 1950.31  5005.4 1948.82
  5010.7 1948.72  5011.1 1948.22  5015.8 1948.22  5016.3 1948.72  5019.9 1950.53
  5034.4 1952.46    5049 1952.07  5098.9 1952.58  5110.2 1953.29  5148.8 1954.29
  5155.1 1955.02  5163.3 1955.01  5169.6 1956.08  5190.4 1956.13  5198.7 1955.18
  5219.5 1956.66    5234 1954.91  5263.1 1954.62  5269.4 1955.85  5298.2 1955.64
#Mann= 5 ,-1 , 0
  4676.5    .035       0  4756.7     .16       0  5010.7     .07       0
  5016.3     .16       0  5110.2     .07       0
Bank Sta=5010.7,5016.3
XS Rating Curve= 0 ,0
Exp/Cntr=0.3,0.1

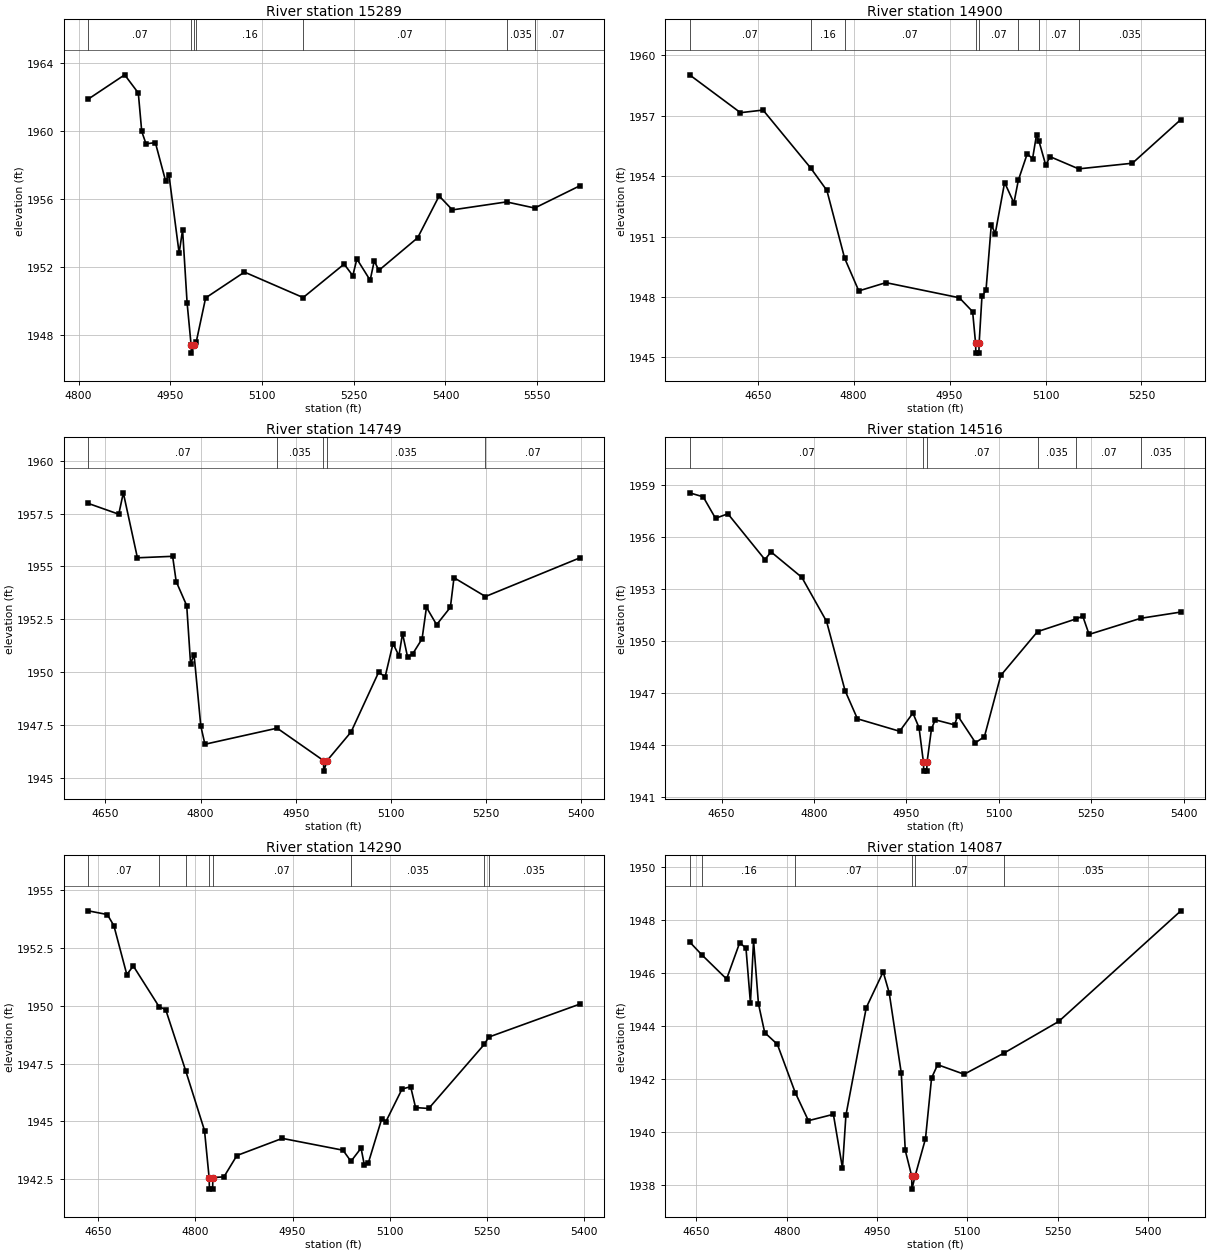
Type RM Length L Ch R = 1 ,15289   ,389,389,389
BEGIN DESCRIPTION:
Elm 01 24 15288.56
END DESCRIPTION:
XS GIS Cut Line= 3
      1535170.72      6806251.94      1535337.78      6806167.32
      1535795.71      6805754.96
#Sta/Elev= 30
  4815.7 1961.87  4875.3  1963.3  4897.6 1962.23  4903.2 1959.97  4910.2 1959.24
  4925.5 1959.31  4942.2 1957.06  4947.8 1957.39  4964.4  1952.8    4970 1954.18
  4977.4 1949.88  4983.9 1947.42  4984.4 1946.92  4989.5 1947.42  4992.3 1947.57
  5007.7 1950.17  5071.2 1951.69  5167.2 1950.19  5234.2 1952.16  5248.4 1951.48
  5255.1 1952.46  5276.8 1951.21  5283.5 1952.35    5291 1951.79  5354.5 1953.71
  5389.6 1956.17  5411.3 1955.35  5499.8 1955.82  5545.9 1955.46  5619.2 1956.76
#Mann= 7 ,-1 , 0
  4815.7     .07       0  4983.9     .07       0  4989.5     .07       0
  4992.3     .16       0  5167.2     .07       0  5499.8    .035       0
  5545.9     .07       0
Bank Sta=4983.9,4989.5
XS Rating Curve= 0 ,0
Exp/Cntr=0.3,0.1

Type RM Length L Ch R = 1 ,14900   ,151,151,151
BEGIN DESCRIPTION:
Elm 01 24 14900.38
END DESCRIPTION:
XS GIS Cut Line= 3
      1535300.88      6806334.43      1535602.53      6806104.39
      1535836.88       6805794.1
#Sta/Elev= 30
  4543.4 1959.03    4623 1957.15  4658.3 1957.28  4732.6 1954.41  4758.1 1953.29
  4785.8 1949.93    4808  1948.3  4850.4 1948.71  4965.2 1947.96    4986 1947.27
  4990.6 1945.71  4991.1 1945.21  4995.8 1945.21  4996.2 1945.71  5000.6 1948.03
  5006.9 1948.33  5015.2 1951.58  5021.4 1951.15    5036 1953.68  5050.6 1952.67
  5057.5  1953.8  5071.4 1955.11  5079.7 1954.86  5085.9 1956.05  5089.7 1955.74
  5100.5 1954.53  5106.8 1954.97  5151.8 1954.36  5235.8 1954.64  5311.6 1956.81
#Mann= 8 ,-1 , 0
  4543.4     .07       0  4732.6     .16       0  4785.8     .07       0
  4990.6     .07       0  4996.2     .07       0  5057.5    .035       0
  5089.7     .07       0  5151.8    .035       0
Bank Sta=4990.6,4996.2
XS Rating Curve= 0 ,0
Exp/Cntr=0.3,0.1

Type RM Length L Ch R = 1 ,14749   ,233,233,233
BEGIN DESCRIPTION:
Elm 01 24 14748.66
END DESCRIPTION:
XS GIS Cut Line= 3
      1535355.12      6806343.11      1535693.68      6806180.34
      1536041.56      6805985.88
#Sta/Elev= 30
  4622.9 1957.98    4671 1957.47  4678.2 1958.48  4700.4 1955.41  4755.9 1955.48
  4761.5 1954.29  4778.1 1953.15  4784.2  1950.4  4789.7 1950.84  4800.3 1947.46
  4806.8  1946.6  4920.6 1947.36  4993.6 1945.83  4994.1 1945.33  4999.4 1945.83
  5037.1 1947.18  5080.5    1950  5090.8 1949.79  5103.2 1951.36  5112.5 1950.78
  5118.2 1951.83  5126.1 1950.73  5134.2 1950.87    5149 1951.58  5155.9 1953.07
  5171.9 1952.25  5193.6 1953.07  5199.3 1954.47  5248.9 1953.58  5397.1  1955.4
#Mann= 5 ,-1 , 0
  4622.9     .07       0  4920.6    .035       0  4993.6    .035       0
  4999.4    .035       0  5248.9     .07       0
Bank Sta=4993.6,4999.4
XS Rating Curve= 0 ,0
Exp/Cntr=0.3,0.1

Type RM Length L Ch R = 1 ,14516   ,226,226,226
BEGIN DESCRIPTION:
Elm 01 24 14515.95
END DESCRIPTION:
XS GIS Cut Line= 3
      1535352.93       6806401.7      1535752.27        6806380.
      1536140.36      6806293.27
#Sta/Elev= 30
  4597.9 1958.56    4620 1958.33    4640 1957.09  4660.1 1957.35  4720.2 1954.71
  4730.2 1955.15  4780.2 1953.68  4820.3 1951.14  4850.3 1947.15  4870.4 1945.52
    4939  1944.8  4960.5 1945.85  4970.5    1945  4977.6    1943  4978.1  1942.5
    4983  1942.5  4983.4    1943  4990.6 1944.93  4996.7 1945.46  5028.1 1945.17
  5033.2  1945.7  5062.1 1944.14  5076.6 1944.49  5103.1 1948.02  5162.8 1950.55
  5225.8 1951.29  5236.3 1951.44  5246.5 1950.39  5330.4 1951.32  5395.5 1951.68
#Mann= 6 ,-1 , 0
  4597.9     .07       0  4977.6     .07       0  4983.4     .07       0
  5162.8    .035       0  5225.8     .07       0  5330.4    .035       0
Bank Sta=4977.6,4983.4
XS Rating Curve= 0 ,0
Exp/Cntr=0.3,0.1

Type RM Length L Ch R = 1 ,14290   ,203,203,203
BEGIN DESCRIPTION:
Elm 01 24 14290.06
END DESCRIPTION:
XS GIS Cut Line= 3
      1535435.47      6806601.35      1535800.02       6806590.5
       1536177.6      6806477.66
#Sta/Elev= 30
  4634.4 1954.09  4663.9 1953.93    4674 1953.45    4694 1951.34    4704 1951.71
  4743.9 1949.95    4754 1949.83  4784.9 1947.19    4814 1944.61  4821.1 1942.58
  4821.6 1942.08  4826.5 1942.08  4826.9 1942.58    4844 1942.61    4864 1943.53
  4934.1 1944.27  5027.9 1943.76  5040.2 1943.28  5055.8 1943.85    5061  1943.1
  5066.9  1943.2  5087.8 1945.12  5094.1 1944.99  5119.1  1946.4  5132.4  1946.5
    5140  1945.6  5160.3 1945.56  5246.2 1948.33  5252.9 1948.64  5393.2 1950.06
#Mann= 8 ,-1 , 0
  4634.4     .07       0  4743.9     .16       0  4784.9     .07       0
  4821.1     .07       0  4826.9     .07       0  5040.2    .035       0
  5246.2     .07       0  5252.9    .035       0
Bank Sta=4821.1,4826.9
XS Rating Curve= 0 ,0
Exp/Cntr=0.3,0.1

Type RM Length L Ch R = 1 ,14087   ,303,303,303
BEGIN DESCRIPTION:
Elm 01 24 14133.8
END DESCRIPTION:
XS GIS Cut Line= 3
      1535454.72      6806715.49      1535754.06       6806798.2
       1536256.8      6806744.99
#Sta/Elev= 30
  4638.5 1947.17  4658.5 1946.69    4700 1945.77  4721.8 1947.14  4732.2 1946.93
  4739.6 1944.87  4744.8 1947.21  4752.9 1944.84  4763.3 1943.75  4784.3 1943.31
    4814 1941.49  4835.9 1940.43  4877.4 1940.67  4892.5 1938.64  4898.2 1940.63
    4932 1944.69  4960.1 1946.04  4970.1 1945.25  4990.2 1942.22  4996.8 1939.31
  5007.4 1938.35  5007.9 1937.85  5013.2 1938.35  5030.4 1939.75  5040.5 1942.04
  5050.6 1942.54  5094.6 1942.18    5161 1942.98  5251.7 1944.17  5454.6 1948.34
#Mann= 6 ,-1 , 0
  4638.5     .07       0  4658.5     .16       0    4814     .07       0
  5007.4     .07       0  5013.2     .07       0    5161    .035       0
Bank Sta=5007.4,5013.2
XS Rating Curve= 0 ,0
Exp/Cntr=0.3,0.1

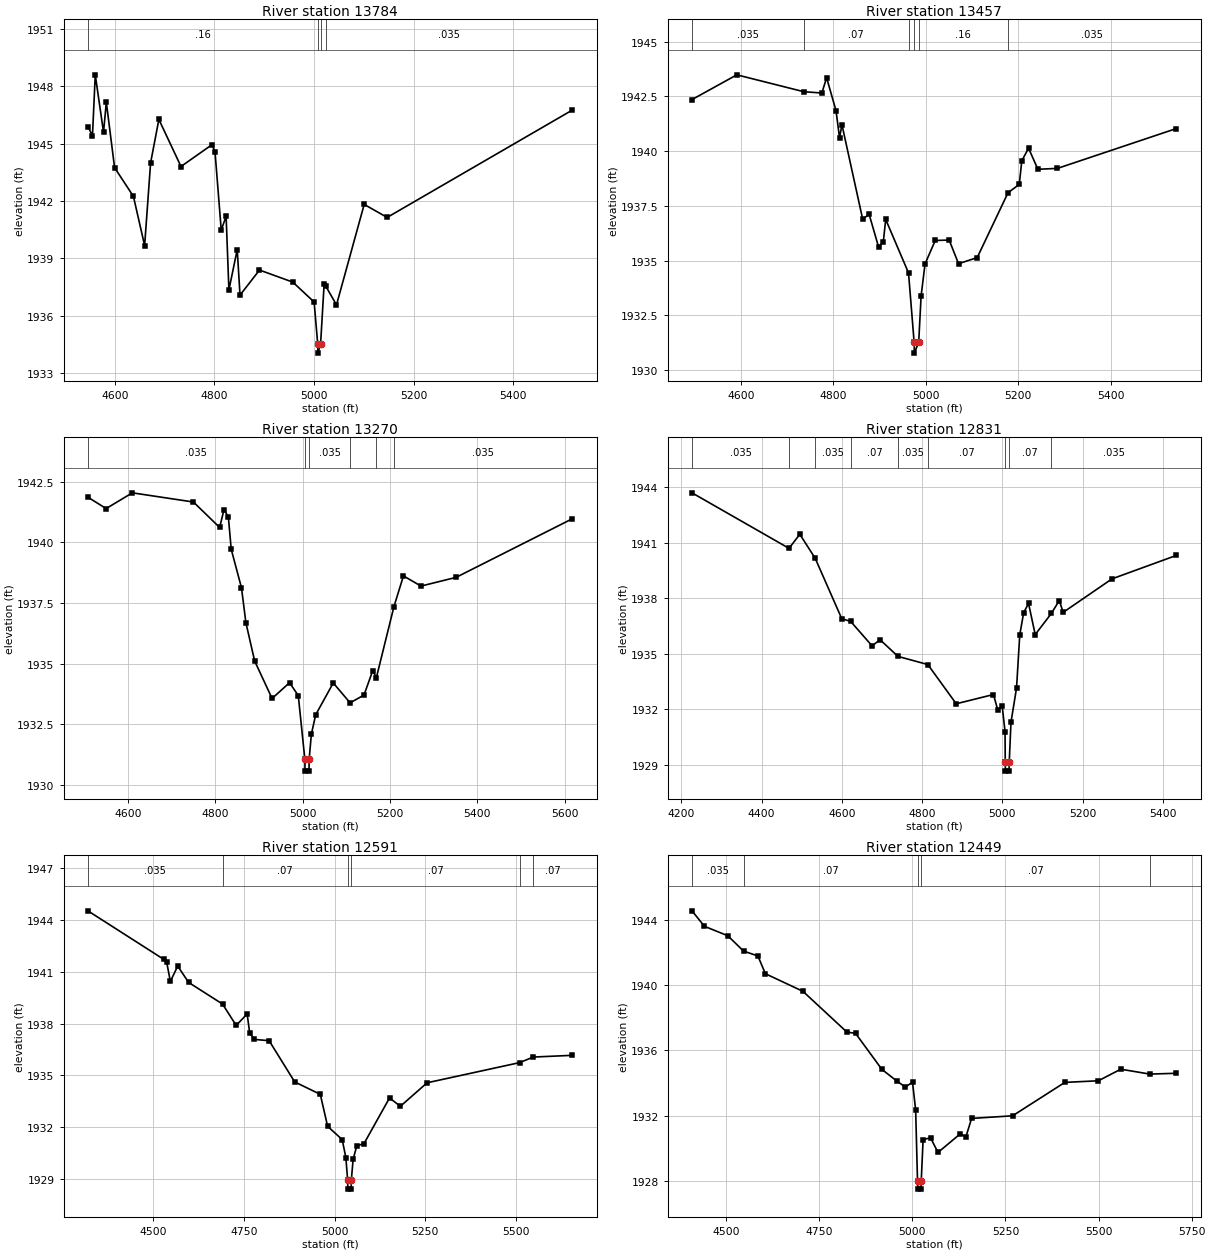
Type RM Length L Ch R = 1 ,13784   ,327,327,327
BEGIN DESCRIPTION:
Elm 01 24 13774.35
END DESCRIPTION:
XS GIS Cut Line= 4
      1535504.86      6806766.61       1535618.4      6806988.36
      1535771.44      6807065.38      1536320.97      6807119.05
#Sta/Elev= 30
    4546 1945.89  4555.2 1945.41  4560.8 1948.59  4577.4 1945.59    4583 1947.16
  4599.6 1943.74  4637.4 1942.24  4659.9 1939.67  4671.9 1943.99  4688.5 1946.26
  4732.9  1943.8  4795.1 1944.94  4801.2 1944.57  4813.7 1940.48  4823.5  1941.2
  4829.1 1937.35  4845.8 1939.46  4851.4 1937.08  4890.5 1938.39  4957.4 1937.76
  5000.2 1936.72  5007.3 1934.55  5007.8 1934.05  5013.2 1934.55  5020.3 1937.67
  5023.5 1937.55  5045.1 1936.57  5100.7 1941.82  5146.8 1941.14  5518.6 1946.75
#Mann= 4 ,-1 , 0
    4546     .16       0  5007.3     .07       0  5013.2     .16       0
  5023.5    .035       0
Bank Sta=5007.3,5013.2
XS Rating Curve= 0 ,0
Exp/Cntr=0.3,0.1

Type RM Length L Ch R = 1 ,13457   ,187,187,187
BEGIN DESCRIPTION:
Elm 01 24 13456.54
END DESCRIPTION:
XS GIS Cut Line= 3
      1535110.18      6807338.89      1535606.61      6807234.91
      1536141.67      6807308.48
#Sta/Elev= 30
  4494.6 1942.35  4591.5 1943.48  4736.2 1942.71  4775.4 1942.65  4785.6 1943.35
    4806 1941.84  4813.6  1940.6  4818.7 1941.21  4863.5  1936.9  4877.6 1937.11
    4898 1935.62  4908.2 1935.86  4913.4 1936.88  4962.7 1934.44  4974.8 1931.28
  4975.3 1930.78  4984.7 1931.28  4989.9 1933.39  4998.4 1934.85  5020.4 1935.92
  5050.6 1935.94  5070.8 1934.86  5111.2 1935.14  5177.8  1938.1  5202.1 1938.48
  5207.6 1939.56  5222.2 1940.13  5242.4 1939.17  5284.6 1939.21  5541.9 1941.03
#Mann= 6 ,-1 , 0
  4494.6    .035       0  4736.2     .07       0  4962.7     .16       0
  4974.8     .07       0  4984.7     .16       0  5177.8    .035       0
Bank Sta=4974.8,4984.7
XS Rating Curve= 0 ,0
Exp/Cntr=0.3,0.1

Type RM Length L Ch R = 1 ,13270   ,439,439,439
BEGIN DESCRIPTION:
Elm 01 24 13270.46
END DESCRIPTION:
XS GIS Cut Line= 3
      1535063.21      6807399.26      1535593.19       6807389.2
      1536170.01      6807332.19
#Sta/Elev= 30
  4507.8 1941.87  4549.6  1941.4  4609.6 1942.05  4749.6 1941.67  4809.6 1940.62
  4819.6 1941.36  4829.6 1941.05  4836.1 1939.72  4859.6 1938.13  4869.7 1936.69
  4889.7 1935.11  4929.7 1933.56  4969.7 1934.21  4989.7 1933.68  5004.7 1931.06
  5005.2 1930.56  5014.2 1930.56  5014.7 1931.06  5019.7 1932.09  5029.7 1932.89
  5069.8  1934.2  5108.4 1933.38  5140.2  1933.7  5160.3 1934.71  5168.6 1934.42
  5208.8 1937.35  5230.6 1938.62  5270.8  1938.2  5351.2 1938.56  5617.5 1940.98
#Mann= 6 ,-1 , 0
  4507.8    .035       0  5004.7    .035       0  5014.7    .035       0
  5108.4     .07       0  5168.6     .16       0  5208.8    .035       0
Bank Sta=5004.7,5014.7
XS Rating Curve= 0 ,0
Exp/Cntr=0.3,0.1

Type RM Length L Ch R = 1 ,12831   ,240,240,240
BEGIN DESCRIPTION:
Elm 01 24 12831.04
END DESCRIPTION:
XS GIS Cut Line= 3
      1535046.43       6807637.4      1535653.57      6807613.92
      1536201.82      6807369.88
#Sta/Elev= 30
  4226.5  1943.7  4468.4  1940.7  4495.3 1941.46  4533.7 1940.16  4599.8  1936.9
  4622.1 1936.75  4675.4 1935.43  4695.4 1935.76    4740 1934.86  4814.4 1934.42
  4885.2  1932.3    4978  1932.8  4989.1 1931.94  4999.8 1932.18  5006.9 1930.79
  5007.4 1929.16  5007.9 1928.66  5016.9 1928.66  5017.4 1929.16  5021.7  1931.3
  5035.6 1933.16  5043.6 1936.03  5053.4 1937.23  5065.5 1937.72  5082.1 1936.04
  5122.3 1937.18  5142.1 1937.88  5151.8 1937.24  5273.5 1939.05  5434.2 1940.32
#Mann= 9 ,-1 , 0
  4226.5    .035       0  4468.4     .07       0  4533.7    .035       0
  4622.1     .07       0    4740    .035       0  4814.4     .07       0
  5007.4     .07       0  5017.4     .07       0  5122.3    .035       0
Bank Sta=5007.4,5017.4
XS Rating Curve= 0 ,0
Exp/Cntr=0.3,0.1

Type RM Length L Ch R = 1 ,12591   ,142,142,142
BEGIN DESCRIPTION:
Elm 01 24 12590.99
END DESCRIPTION:
XS GIS Cut Line= 3
      1534989.46      6807647.46      1535660.27      6807731.31
      1536317.66      6807684.36
#Sta/Elev= 30
  4320.2 1944.53  4529.2 1941.72  4537.4 1941.55  4547.5 1940.44  4567.7 1941.33
  4597.9 1940.38  4691.3 1939.13  4728.9 1937.89  4759.1 1938.56  4766.1 1937.45
  4779.3 1937.08  4819.6 1937.01  4890.1 1934.62  4960.7  1933.9  4980.8 1932.05
    5021 1931.28  5031.1 1930.24  5036.1 1928.91  5036.6 1928.41  5045.6 1928.41
  5046.1 1928.91  5051.1 1930.13  5061.1 1930.91  5081.2 1931.05  5151.4 1933.69
  5181.4 1933.21    5255 1934.57  5510.4 1935.74  5547.4 1936.06  5655.3 1936.16
#Mann= 6 ,-1 , 0
  4320.2    .035       0  4691.3     .07       0  5036.1     .07       0
  5046.1     .07       0  5510.4    .035       0  5547.4     .07       0
Bank Sta=5036.1,5046.1
XS Rating Curve= 0 ,0
Exp/Cntr=0.3,0.1

Type RM Length L Ch R = 1 ,12449   ,302,302,302
BEGIN DESCRIPTION:
Elm 01 24 12449.47
END DESCRIPTION:
XS GIS Cut Line= 3
      1535019.64      6807778.27      1535603.25      6807855.42
      1536314.31      6807892.31
#Sta/Elev= 30
  4408.5 1944.57  4441.9 1943.62  4504.7 1943.04  4546.9  1942.1  4585.4  1941.8
  4605.6 1940.71  4706.4 1939.63  4824.3 1937.13  4847.6 1937.05  4918.3 1934.84
  4958.6 1934.12  4981.3 1933.76  5000.6 1934.05    5009 1932.35    5014 1927.99
  5014.5 1927.49  5023.5 1927.49    5024 1927.99    5029 1930.53    5049 1930.64
    5069 1929.74  5129.1 1930.89  5143.8 1930.69  5159.2 1931.83  5269.3 1931.99
  5409.5 1934.04  5499.6 1934.14  5559.7 1934.85  5637.8 1934.55  5709.2  1934.6
#Mann= 5 ,-1 , 0
  4408.5    .035       0  4546.9     .07       0    5014     .07       0
    5024     .07       0  5637.8    .035       0
Bank Sta=5014,5024
XS Rating Curve= 0 ,0
Exp/Cntr=0.3,0.1

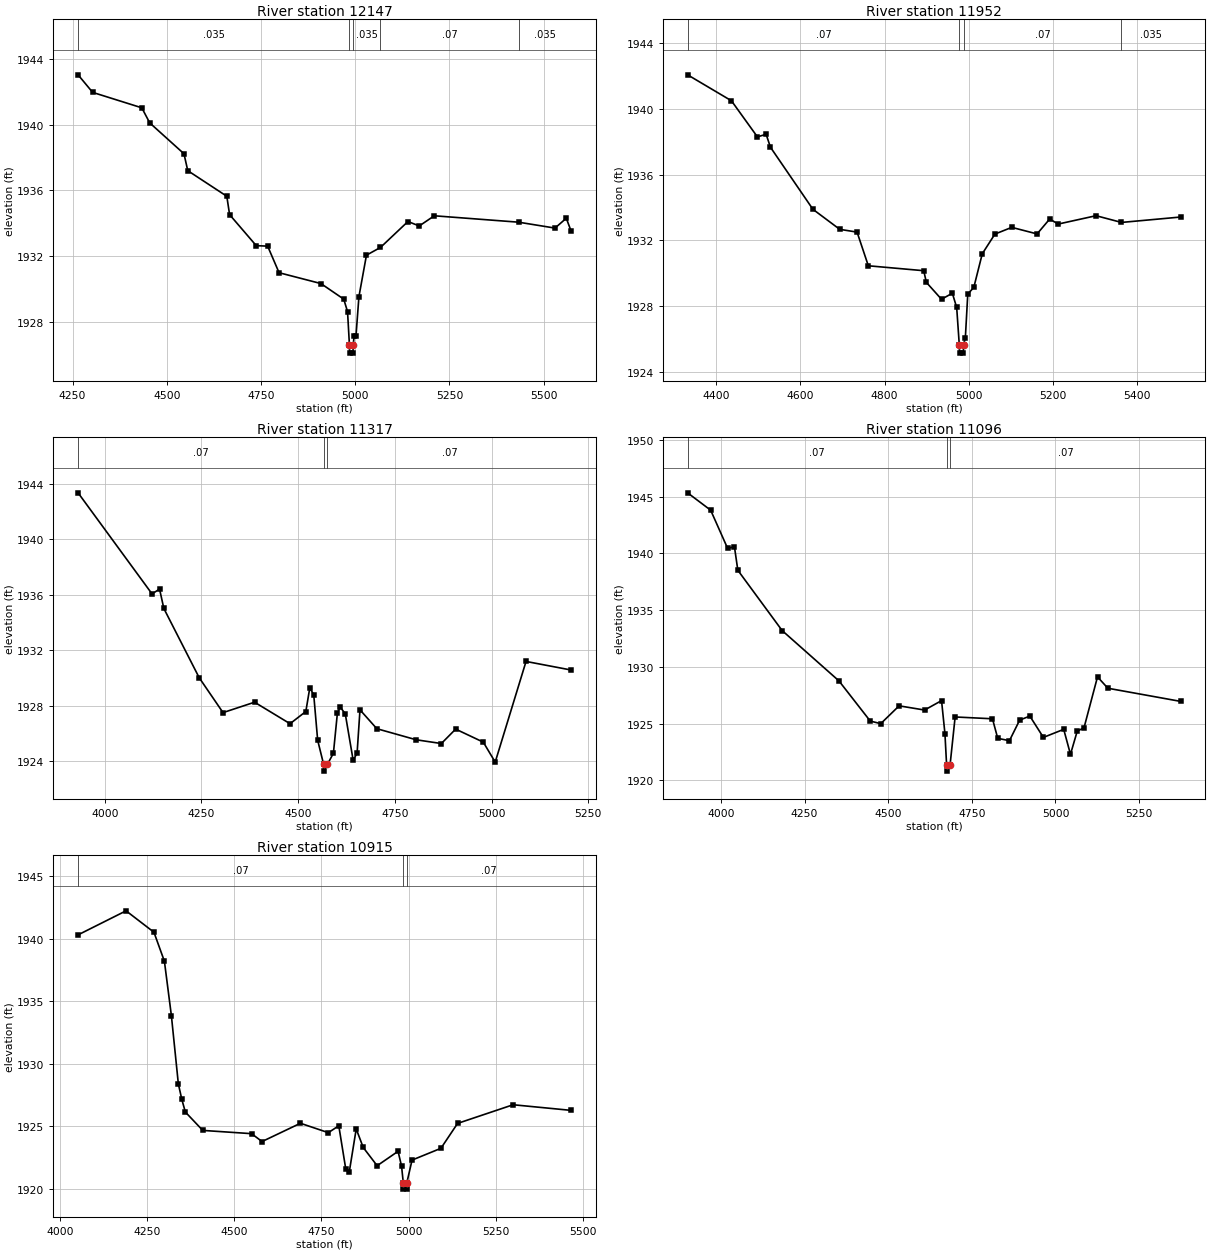
Type RM Length L Ch R = 1 ,12147   ,195,195,195
BEGIN DESCRIPTION:
Elm 01 24 12146.6
END DESCRIPTION:
XS GIS Cut Line= 3
      1535076.64      6807939.27       1535804.5      6808039.89
      1536378.06      6808060.02
#Sta/Elev= 30
  4264.5 1943.04  4303.2 1941.97  4433.6 1941.03  4454.7 1940.11  4545.5 1938.23
  4555.6  1937.2  4659.2 1935.64  4666.6 1934.52  4737.3 1932.63  4767.6  1932.6
  4797.9 1930.98  4908.9 1930.32  4969.5 1929.37  4979.6 1928.61  4984.6 1926.58
  4985.1 1926.08  4994.2 1926.08  4994.7 1926.58    4997 1927.12    5002 1927.12
  5009.8 1929.52  5029.8 1932.05    5067 1932.52  5139.9  1934.1  5169.9 1933.83
  5209.9 1934.45  5433.4 1934.06  5530.1  1933.7  5560.1  1934.3  5573.2  1933.5
#Mann= 5 ,-1 , 0
  4264.5    .035       0  4984.6    .035       0  4994.7    .035       0
    5067     .07       0  5433.4    .035       0
Bank Sta=4984.6,4994.7
XS Rating Curve= 0 ,0
Exp/Cntr=0.3,0.1

Type RM Length L Ch R = 1 ,11952   ,635,635,635
BEGIN DESCRIPTION:
Elm 01 24 11951.73
END DESCRIPTION:
XS GIS Cut Line= 3
       1535153.8      6808053.31      1535801.15       6808207.6
      1536305.99      6808216.28
#Sta/Elev= 30
  4332.7 1942.09  4436.7 1940.51  4498.4 1938.31    4519 1938.47  4529.3 1937.68
  4630.1  1933.9  4693.7 1932.68  4734.9 1932.51  4761.6 1930.46  4893.1 1930.16
  4899.3 1929.45  4935.3 1928.42    4961 1928.79  4971.3 1927.92  4977.5 1925.64
    4978 1925.14  4987.1 1925.14  4987.6 1925.64  4991.9 1926.09  4997.6 1928.73
    5012 1929.15    5032 1931.19    5062 1932.39    5102  1932.8  5162.1  1932.4
  5192.1 1933.31  5212.1    1933  5302.1 1933.51  5362.4  1933.1  5503.1 1933.43
#Mann= 4 ,-1 , 0
  4332.7     .07       0  4977.5     .07       0  4987.6     .07       0
  5362.4    .035       0
Bank Sta=4977.5,4987.6
XS Rating Curve= 0 ,0
Exp/Cntr=0.3,0.1

Type RM Length L Ch R = 1 ,11317   ,221,221,221
BEGIN DESCRIPTION:
Elm 01 24 11316.61
END DESCRIPTION:
XS GIS Cut Line= 3
      1535207.46      6808281.38      1536260.66      6808489.34
      1536461.82      6808488.58
#Sta/Elev= 30
  3931.1 1943.34  4122.3 1936.05  4141.7  1936.4  4152.8    1935  4244.3    1930
  4305.8 1927.49  4387.3 1928.24    4479 1926.69  4519.8 1927.57    4530 1929.27
  4540.2 1928.79  4550.4  1925.5  4565.7 1923.77  4566.2 1923.27  4575.8 1923.77
  4591.1 1924.56  4601.3 1927.43  4608.5 1927.89  4621.7 1927.41  4642.1 1924.06
  4652.3 1924.56  4659.8 1927.69  4703.3 1926.33  4805.2 1925.53  4870.1 1925.26
  4907.1  1926.3  4978.5 1925.36  5009.3 1923.92    5089 1931.18  5205.8 1930.56
#Mann= 3 ,-1 , 0
  3931.1     .07       0  4565.7     .07       0  4575.8     .07       0
Bank Sta=4565.7,4575.8
XS Rating Curve= 0 ,0
Exp/Cntr=0.3,0.1

Type RM Length L Ch R = 1 ,11096   ,181,181,181
BEGIN DESCRIPTION:
Elm 01 24 11096.41
END DESCRIPTION:
XS GIS Cut Line= 3
      1535147.07      6808475.92      1536220.41       6808660.4
       1536601.4      6808713.87
#Sta/Elev= 30
  3900.6 1945.33  3969.5  1943.8  4020.3 1940.43  4040.5 1940.59  4050.7 1938.51
  4183.1  1933.2  4352.8 1928.77  4446.4 1925.23  4477.8    1925  4532.7 1926.57
  4608.8  1926.2  4659.5 1927.03  4669.6 1924.13  4674.7 1921.32  4675.2 1920.82
  4684.8 1921.32  4700.1 1925.59  4811.7 1925.43  4827.4 1923.71  4862.4  1923.5
  4892.9 1925.31  4923.3 1925.67  4963.9 1923.79  5024.6  1924.5  5044.8  1922.3
    5065 1924.34  5085.3 1924.64  5125.6 1929.12  5156.6 1928.12  5374.4 1926.96
#Mann= 3 ,-1 , 0
  3900.6     .07       0  4674.7     .07       0  4684.8     .07       0
Bank Sta=4674.7,4684.8
XS Rating Curve= 0 ,0
Exp/Cntr=0.3,0.1

Type RM Length L Ch R = 1 ,10915   ,352,352,352
BEGIN DESCRIPTION:
Elm 01 24 10914.76
END DESCRIPTION:
XS GIS Cut Line= 3
      1535207.47      6808794.57      1536156.68      6808814.69
      1536619.51      6808858.29
#Sta/Elev= 30
    4052  1940.3  4189.6 1942.22  4269.6 1940.51  4299.6 1938.19  4319.6 1933.85
  4339.6 1928.39  4349.6 1927.15  4359.6 1926.15  4409.6 1924.68  4549.6 1924.42
  4579.6 1923.79  4689.7 1925.25  4769.7  1924.5  4799.7 1925.05  4819.7  1921.6
  4829.7 1921.35  4849.7  1924.8  4869.7 1923.32  4909.7 1921.86  4969.7 1923.01
  4979.7 1921.83  4984.7 1920.49  4985.2 1919.99  4994.3 1919.99  4994.8 1920.49
  5009.8 1922.31  5092.6 1923.25  5140.4 1925.24  5299.7 1926.73  5466.3 1926.28
#Mann= 3 ,-1 , 0
    4052     .07       0  4984.7     .07       0  4994.8     .07       0
Bank Sta=4984.7,4994.8
XS Rating Curve= 0 ,0
Exp/Cntr=0.3,0.1