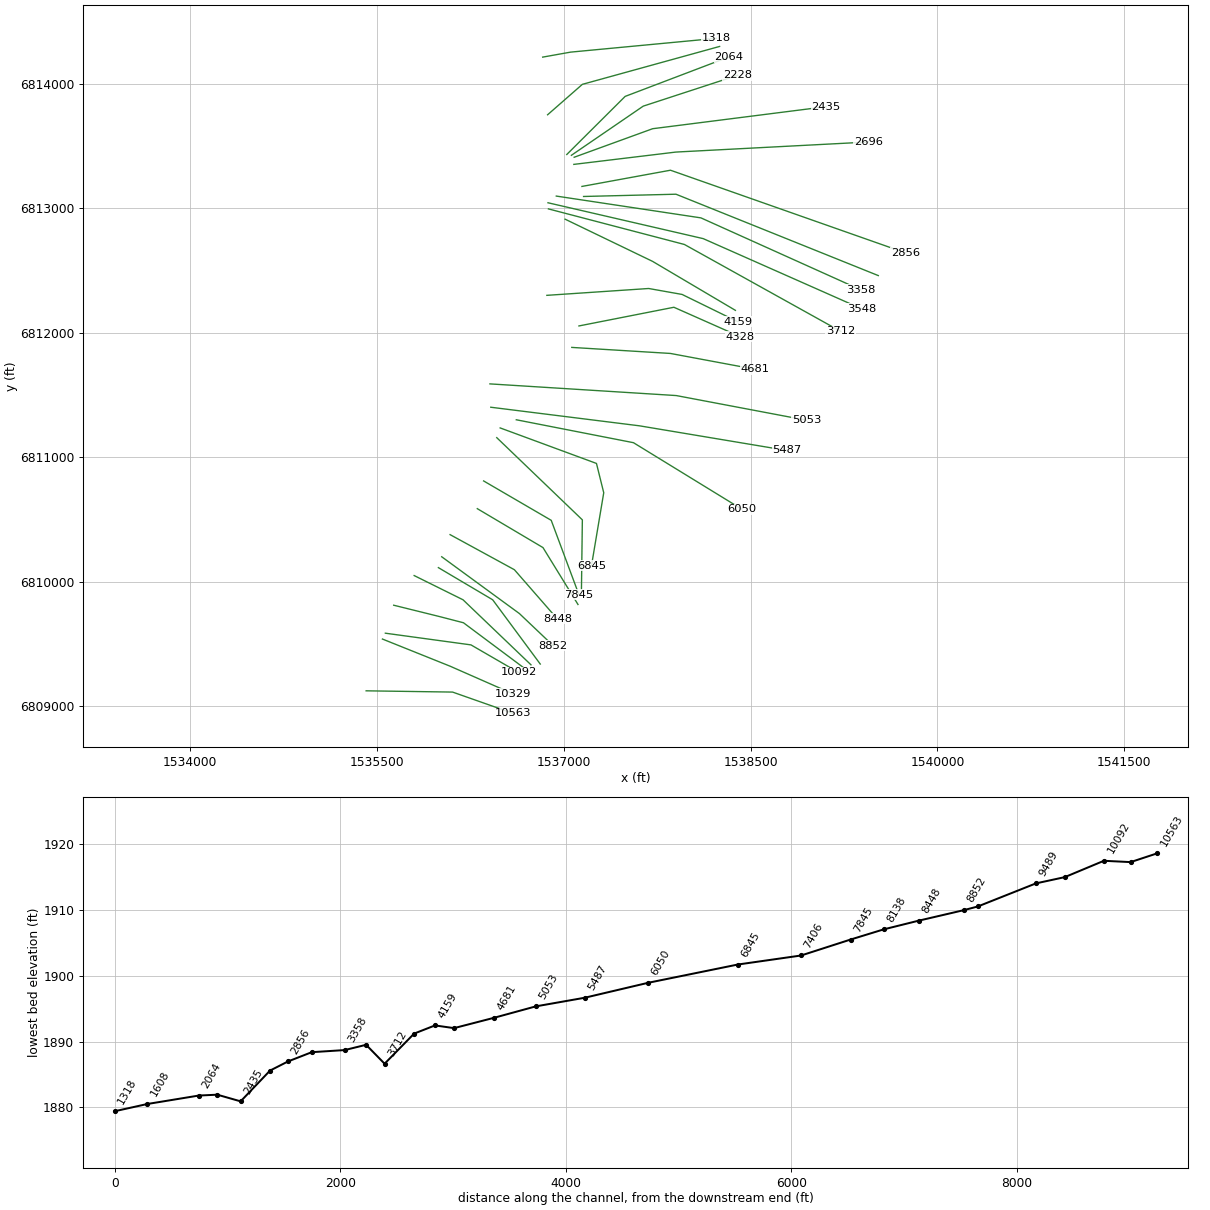
HEC-RAS study Elm 01 24.prj: Elm 01 24 Base Level Engineering

--- Elm 01 24.g01 (geometry) --- (continued)

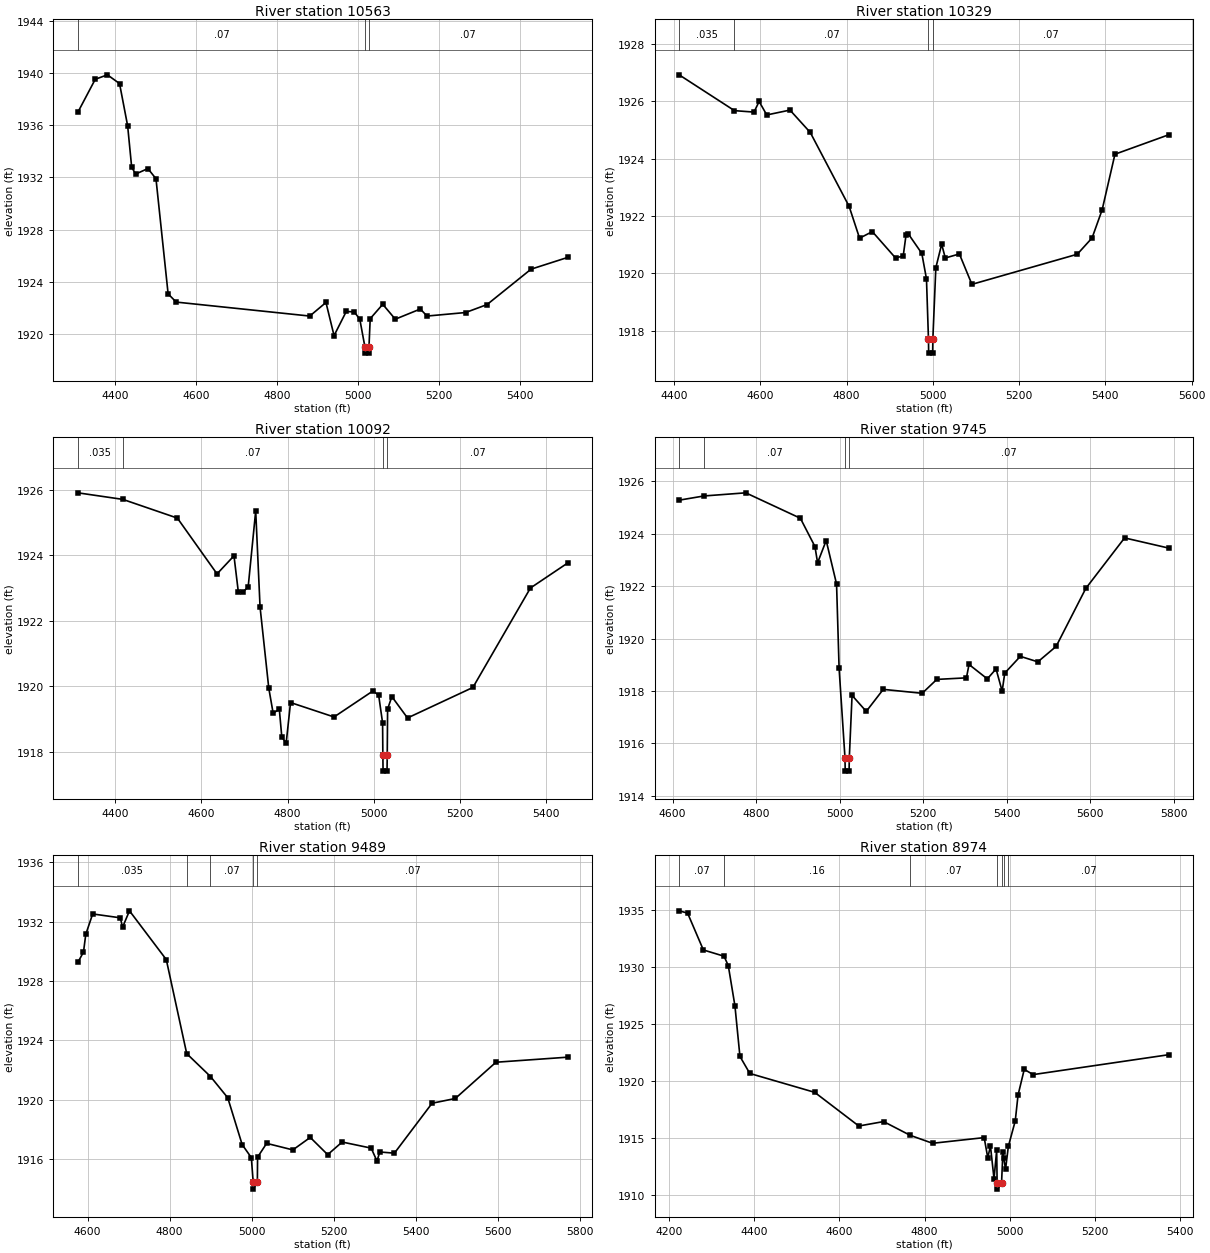
Type RM Length L Ch R = 1 ,10563   ,234,234,234
BEGIN DESCRIPTION:
Elm 01 24 10563.44
END DESCRIPTION:
XS GIS Cut Line= 3
      1535412.12      6809123.27      1536106.37       6809113.2
      1536592.74      6808942.14
#Sta/Elev= 30
  4307.6    1937  4350.5 1939.52  4380.5 1939.86  4410.5 1939.19  4430.5 1935.95
  4440.5 1932.77  4450.5 1932.26  4480.5 1932.68  4500.5  1931.9  4530.5 1923.08
  4550.5 1922.45  4880.5 1921.38  4920.5 1922.42  4940.5 1919.88  4970.6 1921.73
  4990.6  1921.7  5004.2 1921.12  5016.6 1919.04  5017.1 1918.54  5026.3 1918.54
  5026.8 1919.04  5029.8 1921.18  5060.8 1922.28  5091.8 1921.14  5153.7 1921.92
  5170.1 1921.38  5265.5 1921.65  5318.5 1922.26  5427.1 1924.97  5517.5 1925.87
#Mann= 3 ,-1 , 0
  4307.6     .07       0  5016.6     .07       0  5026.8     .07       0
Bank Sta=5016.6,5026.8
XS Rating Curve= 0 ,0
Exp/Cntr=0.3,0.1

Type RM Length L Ch R = 1 ,10329   ,237,237,237
BEGIN DESCRIPTION:
Elm 01 24 10329.4
END DESCRIPTION:
XS GIS Cut Line= 3
      1535542.91      6809539.16      1536086.24      6809321.16
      1536589.36      6809099.79
#Sta/Elev= 30
    4412 1926.93  4540.3 1925.68  4585.5 1925.63  4597.4    1926  4615.1 1925.53
  4668.9  1925.7  4715.9 1924.92    4806 1922.34  4830.2 1921.23  4859.8 1921.46
  4913.6 1920.54  4931.4 1920.61  4937.8 1921.33  4943.2 1921.38  4974.5  1920.7
  4985.3 1919.81  4989.9 1917.72  4990.4 1917.22  4999.6 1917.22  5000.1 1917.72
    5007  1920.2  5020.5 1921.02  5028.9 1920.54  5061.6 1920.68  5090.6 1919.62
  5334.8 1920.67  5369.2 1921.24  5392.5 1922.22  5422.2 1924.16  5547.1 1924.84
#Mann= 4 ,-1 , 0
    4412    .035       0  4540.3     .07       0  4989.9     .07       0
  5000.1     .07       0
Bank Sta=4989.9,5000.1
XS Rating Curve= 0 ,0
Exp/Cntr=0.3,0.1

Type RM Length L Ch R = 1 ,10092   ,347,347,347
BEGIN DESCRIPTION:
Elm 01 24 10091.55
END DESCRIPTION:
XS GIS Cut Line= 3
      1535566.38      6809586.13      1536253.95      6809492.22
      1536636.33      6809270.84
#Sta/Elev= 30
  4313.7  1925.9    4418  1925.7  4544.4 1925.13  4636.4 1923.43  4675.7 1923.98
  4685.7 1922.89  4695.8 1922.87  4708.6 1923.03  4726.1 1925.35  4736.2 1922.42
  4756.4 1919.95  4766.5 1919.19  4780.9  1919.3  4786.7 1918.45  4796.8 1918.28
  4806.9 1919.51  4907.8 1919.07  4997.7 1919.86  5011.2 1919.74  5020.4 1918.89
    5021 1917.92  5021.5 1917.42  5030.7 1917.42  5031.2 1917.92    5032 1919.31
  5041.9 1919.69  5078.2 1919.04  5229.9 1919.97  5363.3    1923  5449.5 1923.76
#Mann= 4 ,-1 , 0
  4313.7    .035       0    4418     .07       0    5021     .07       0
  5031.2     .07       0
Bank Sta=5021,5031.2
XS Rating Curve= 0 ,0
Exp/Cntr=0.3,0.1

Type RM Length L Ch R = 1 ,9745    ,256,256,256
BEGIN DESCRIPTION:
Elm 01 24 9744.97
END DESCRIPTION:
XS GIS Cut Line= 4
      1535633.43      6809810.86      1535999.04       6809720.3
      1536193.58      6809669.99      1536669.82      6809314.48
#Sta/Elev= 30
  4615.9 1925.28  4675.2 1925.44  4775.3 1925.56    4906 1924.59  4940.9 1923.51
  4947.2 1922.89  4967.8 1923.74  4992.6 1922.08  4998.7 1918.86  5012.8 1915.44
  5013.3 1914.94  5022.6 1914.94  5023.1 1915.44  5029.7 1917.83  5063.7 1917.22
  5104.4 1918.06  5197.5 1917.91  5232.5 1918.44  5303.4  1918.5  5309.6 1919.01
  5353.4 1918.46  5374.3 1918.84  5388.9 1917.99  5395.1 1918.68  5432.4 1919.32
  5474.3 1919.11  5518.1  1919.7    5589 1921.91  5681.9 1923.84  5787.8 1923.45
#Mann= 4 ,-1 , 0
  4615.9    .035       0  4675.2     .07       0  5012.8     .07       0
  5023.1     .07       0
Bank Sta=5012.8,5023.1
XS Rating Curve= 0 ,0
Exp/Cntr=0.3,0.1

Type RM Length L Ch R = 1 ,9489    ,515,515,515
BEGIN DESCRIPTION:
Elm 01 24 9488.76
END DESCRIPTION:
XS GIS Cut Line= 3
      1535797.76      6810049.01      1536190.22      6809854.46
      1536736.01      6809332.12
#Sta/Elev= 30
  4576.4 1929.26    4590 1929.94  4595.6 1931.14  4612.4 1932.51  4679.7 1932.25
  4685.3 1931.62  4702.1 1932.72  4791.8 1929.44  4841.6 1923.11  4899.5 1921.57
  4941.6 1920.14  4976.7 1916.99  4999.1 1916.11  5003.5 1914.49    5004 1913.99
  5013.8 1914.49  5014.3 1916.14  5036.4 1917.07  5100.3 1916.63  5142.7 1917.47
  5185.2 1916.31  5220.4 1917.16  5291.2 1916.75  5305.3 1915.88  5312.2 1916.49
  5347.8 1916.41  5439.6 1919.77  5496.2 1920.09  5595.3 1922.53  5769.9 1922.87
#Mann= 5 ,-1 , 0
  4576.4    .035       0  4841.6     .16       0  4899.5     .07       0
  5003.5     .07       0  5013.8     .07       0
Bank Sta=5003.5,5013.8
XS Rating Curve= 0 ,0
Exp/Cntr=0.3,0.1

Type RM Length L Ch R = 1 ,8974    ,122,122,122
BEGIN DESCRIPTION:
Elm 01 24 8974.17
END DESCRIPTION:
XS GIS Cut Line= 3
      1535992.35      6810112.71      1536428.36      6809854.46
      1536810.37      6809338.42
#Sta/Elev= 30
  4224.1 1934.96  4243.9 1934.76  4280.9 1931.52  4329.4 1930.97  4339.4 1930.14
    4355  1926.6  4366.7 1922.16  4389.9 1920.66  4542.1    1919  4645.6 1916.04
  4703.7 1916.43  4766.2 1915.22  4818.7 1914.52  4939.7 1915.02  4948.1 1913.25
  4954.4 1914.28  4962.8 1911.39    4969 1913.92  4970.1 1910.99  4970.6 1910.49
  4980.4 1910.99  4983.6 1913.73  4985.7 1913.22  4989.8 1912.23  4996.4 1914.25
  5012.6 1916.49  5019.1 1918.75  5033.7 1921.02  5054.6 1920.56  5372.9 1922.31
#Mann= 7 ,-1 , 0
  4224.1     .07       0  4329.4     .16       0  4766.2     .07       0
  4970.1     .07       0  4980.4     .07       0  4985.7     .16       0
  4996.4     .07       0
Bank Sta=4970.1,4980.4
XS Rating Curve= 0 ,0
Exp/Cntr=0.3,0.1

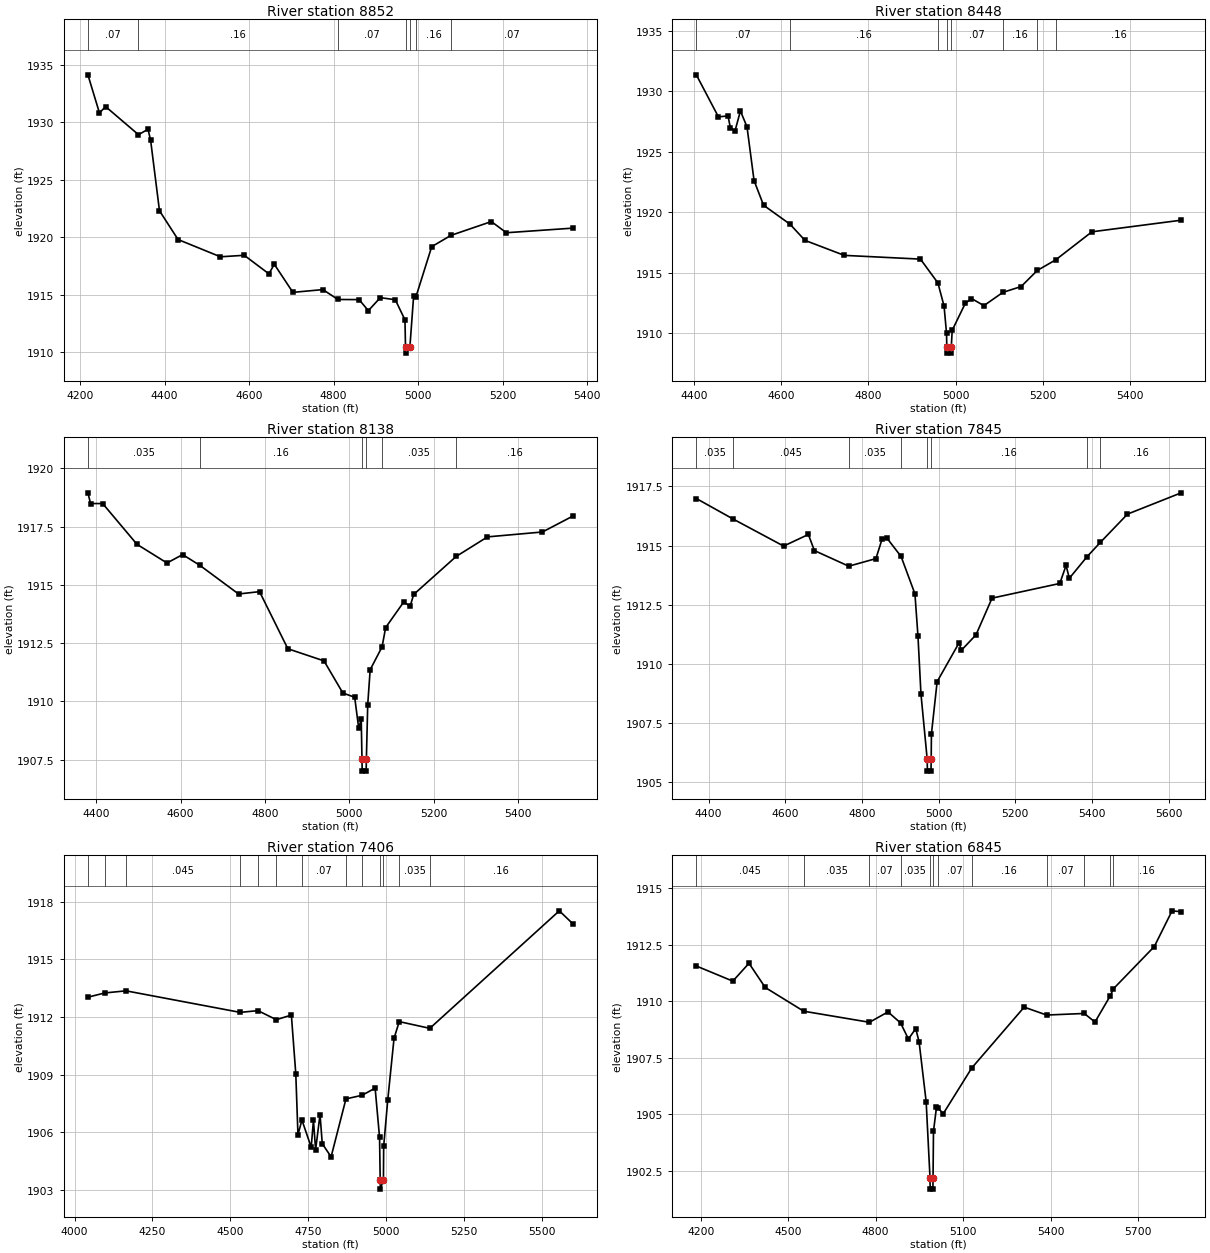
Type RM Length L Ch R = 1 ,8852    ,404,404,404
BEGIN DESCRIPTION:
Elm 01 24 8852.36
END DESCRIPTION:
XS GIS Cut Line= 3
      1536019.15      6810199.94      1536643.03      6809743.78
       1536914.7      6809485.52
#Sta/Elev= 30
  4218.3 1934.12  4245.6 1930.81  4260.2 1931.36    4338 1928.92  4360.6 1929.39
  4366.8 1928.42  4387.7 1922.31  4431.7 1919.81    4532 1918.31  4588.4 1918.44
  4646.7 1916.83  4659.5 1917.66  4703.5 1915.22  4774.5 1915.46  4810.2  1914.6
  4860.2 1914.59  4882.1 1913.63  4910.4 1914.76  4945.9 1914.58  4968.8 1912.83
  4970.1 1910.44  4970.6 1909.94  4980.4 1910.44  4989.3  1914.9  4994.7 1914.82
  5032.1 1919.19  5077.6 1920.17  5173.3 1921.37  5208.9  1920.4    5366  1920.8
#Mann= 7 ,-1 , 0
  4218.3     .07       0    4338     .16       0  4810.2     .07       0
  4970.1     .07       0  4980.4     .07       0  4994.7     .16       0
  5077.6     .07       0
Bank Sta=4970.1,4980.4
XS Rating Curve= 0 ,0
Exp/Cntr=0.3,0.1

Type RM Length L Ch R = 1 ,8448    ,310,310,310
BEGIN DESCRIPTION:
Elm 01 24 8448.07
END DESCRIPTION:
XS GIS Cut Line= 3
      1536086.22      6810377.71      1536602.78      6810095.96
      1536947.03      6809701.57
#Sta/Elev= 30
  4405.4 1931.36  4456.1 1927.88    4478 1927.96  4483.7 1926.95  4494.1 1926.71
  4506.5 1928.37  4521.6 1927.06  4537.8 1922.61  4559.6 1920.57  4620.2    1919
  4654.6 1917.66  4744.7 1916.42  4919.4 1916.11  4959.4 1914.14  4973.5 1912.23
  4979.2 1909.98  4979.8 1908.83  4980.3 1908.33  4989.6 1908.33  4990.1 1908.83
  4992.2 1910.22  5022.1 1912.44  5036.4 1912.85  5064.9 1912.26  5108.5 1913.36
  5150.3 1913.84  5187.3 1915.17  5229.6 1916.05  5312.6 1918.37  5517.3 1919.33
#Mann= 8 ,-1 , 0
  4405.4     .07       0  4620.2     .16       0  4959.4     .07       0
  4979.8     .07       0  4990.1     .07       0  5108.5     .16       0
  5187.3     .07       0  5229.6     .16       0
Bank Sta=4979.8,4990.1
XS Rating Curve= 0 ,0
Exp/Cntr=0.3,0.1

Type RM Length L Ch R = 1 ,8138    ,293,293,293
BEGIN DESCRIPTION:
Elm 01 24 8138.16
END DESCRIPTION:
XS GIS Cut Line= 3
      1536304.86      6810586.33      1536832.24      6810273.81
      1537113.51      6809816.74
#Sta/Elev= 30
  4380.1 1918.95  4386.4 1918.49  4415.1 1918.49  4496.5 1916.74  4567.6 1915.94
  4604.7  1916.3  4645.5 1915.84  4737.3 1914.61  4787.1 1914.71  4854.2 1912.26
  4939.9 1911.74  4984.7 1910.36  5012.7 1910.18  5022.3 1908.84  5028.2 1909.25
    5030 1907.51  5030.5 1907.01  5039.9 1907.01  5040.4 1907.51  5043.6 1909.86
  5049.4 1911.36  5077.6 1912.34  5086.1 1913.17  5129.1 1914.27  5144.1 1914.08
  5152.6 1914.59  5253.3 1916.22  5327.6 1917.06  5457.9 1917.27  5529.8 1917.95
#Mann= 6 ,-1 , 0
  4380.1    .035       0  4645.5     .16       0    5030     .07       0
  5040.4     .16       0  5077.6    .035       0  5253.3     .16       0
Bank Sta=5030,5040.4
XS Rating Curve= 0 ,0
Exp/Cntr=0.3,0.1

Type RM Length L Ch R = 1 ,7845    ,439,439,439
BEGIN DESCRIPTION:
Elm 01 24 7844.6
END DESCRIPTION:
XS GIS Cut Line= 3
      1536355.63      6810808.99      1536898.64      6810492.56
      1537120.65      6809896.65
#Sta/Elev= 30
    4368 1916.99  4464.3 1916.12  4595.7 1914.98  4660.2 1915.47  4675.9 1914.79
  4765.5 1914.13  4836.4 1914.45  4852.1 1915.26  4864.9 1915.32    4902 1914.54
  4938.1 1912.96    4946 1911.18  4953.8 1908.73  4970.1 1905.97  4970.6 1905.47
    4980 1905.47  4980.5 1905.97  4981.1 1907.04    4996 1909.25  5053.5  1910.9
  5058.8 1910.57  5097.4 1911.23  5139.2 1912.78  5315.8  1913.4  5332.2 1914.16
  5340.8 1913.62  5386.9 1914.53  5421.9 1915.14  5492.4 1916.33  5632.4 1917.23
#Mann= 8 ,-1 , 0
    4368    .035       0  4464.3    .045       0  4765.5    .035       0
    4902     .16       0  4970.1     .07       0  4980.5     .16       0
  5386.9    .035       0  5421.9     .16       0
Bank Sta=4970.1,4980.5
XS Rating Curve= 0 ,0
Exp/Cntr=0.3,0.1

Type RM Length L Ch R = 1 ,7406    ,561,561,561
BEGIN DESCRIPTION:
Elm 01 24 7405.67
END DESCRIPTION:
XS GIS Cut Line= 3
      1536461.18      6811156.59      1537148.64      6810496.47
      1537140.83       6809894.9
#Sta/Elev= 30
  4042.9 1913.03    4097 1913.25  4165.1 1913.36  4531.2 1912.24  4588.2 1912.33
    4647 1911.86  4695.3  1912.1  4709.5 1909.04  4716.4 1905.88  4729.2 1906.64
  4758.9 1905.23  4766.1 1906.63    4773 1905.09  4787.2 1906.93  4794.4 1905.41
  4822.7 1904.73  4870.3 1907.74    4922 1907.93  4963.9  1908.3  4978.1 1905.74
  4980.1 1903.55  4980.6 1903.05  4990.5 1903.55  4991.3 1905.28  5004.5 1907.71
  5024.5 1910.89  5041.2 1911.76  5139.2 1911.41  5554.5 1917.52  5597.6 1916.85
#Mann= 13 ,-1 , 0
  4042.9    .045       0    4097     .07       0  4165.1    .045       0
  4531.2    .035       0  4588.2    .045       0    4647    .035       0
  4729.2     .07       0  4870.3     .16       0    4922     .07       0
  4980.1     .07       0  4990.5     .07       0  5041.2    .035       0
  5139.2     .16       0
Bank Sta=4980.1,4990.5
XS Rating Curve= 0 ,0
Exp/Cntr=0.3,0.1

Type RM Length L Ch R = 1 ,6845    ,795,795,795
BEGIN DESCRIPTION:
Elm 01 24 6845.46
END DESCRIPTION:
XS GIS Cut Line= 4
      1536488.49      6811234.75      1537261.92      6810949.59
      1537320.37      6810714.16      1537221.77      6810127.19
#Sta/Elev= 30
  4185.2 1911.55  4310.3 1910.88  4365.8 1911.67  4421.4  1910.6  4553.3 1909.55
  4778.8 1909.06  4842.3 1909.52  4885.4 1909.03  4912.3 1908.32  4937.4 1908.78
  4948.9 1908.19  4973.1 1905.55  4986.3 1902.18  4986.8 1901.68  4996.2 1901.68
  4996.7 1902.18  4998.2 1904.24  5008.5  1905.3  5015.2 1905.25  5031.8 1905.02
  5129.5 1907.04  5309.1 1909.73    5386 1909.38  5515.1 1909.45  5551.8 1909.07
  5604.2 1910.23  5614.9 1910.54  5755.2 1912.41  5816.1 1913.99  5847.3 1913.95
#Mann= 12 ,-1 , 0
  4185.2    .045       0  4553.3    .035       0  4778.8     .07       0
  4885.4    .035       0  4986.3    .035       0  4996.7    .035       0
  5015.2     .07       0  5129.5     .16       0    5386     .07       0
  5515.1    .035       0  5604.2     .07       0  5614.9     .16       0
Bank Sta=4986.3,4996.7
XS Rating Curve= 0 ,0
Exp/Cntr=0.3,0.1

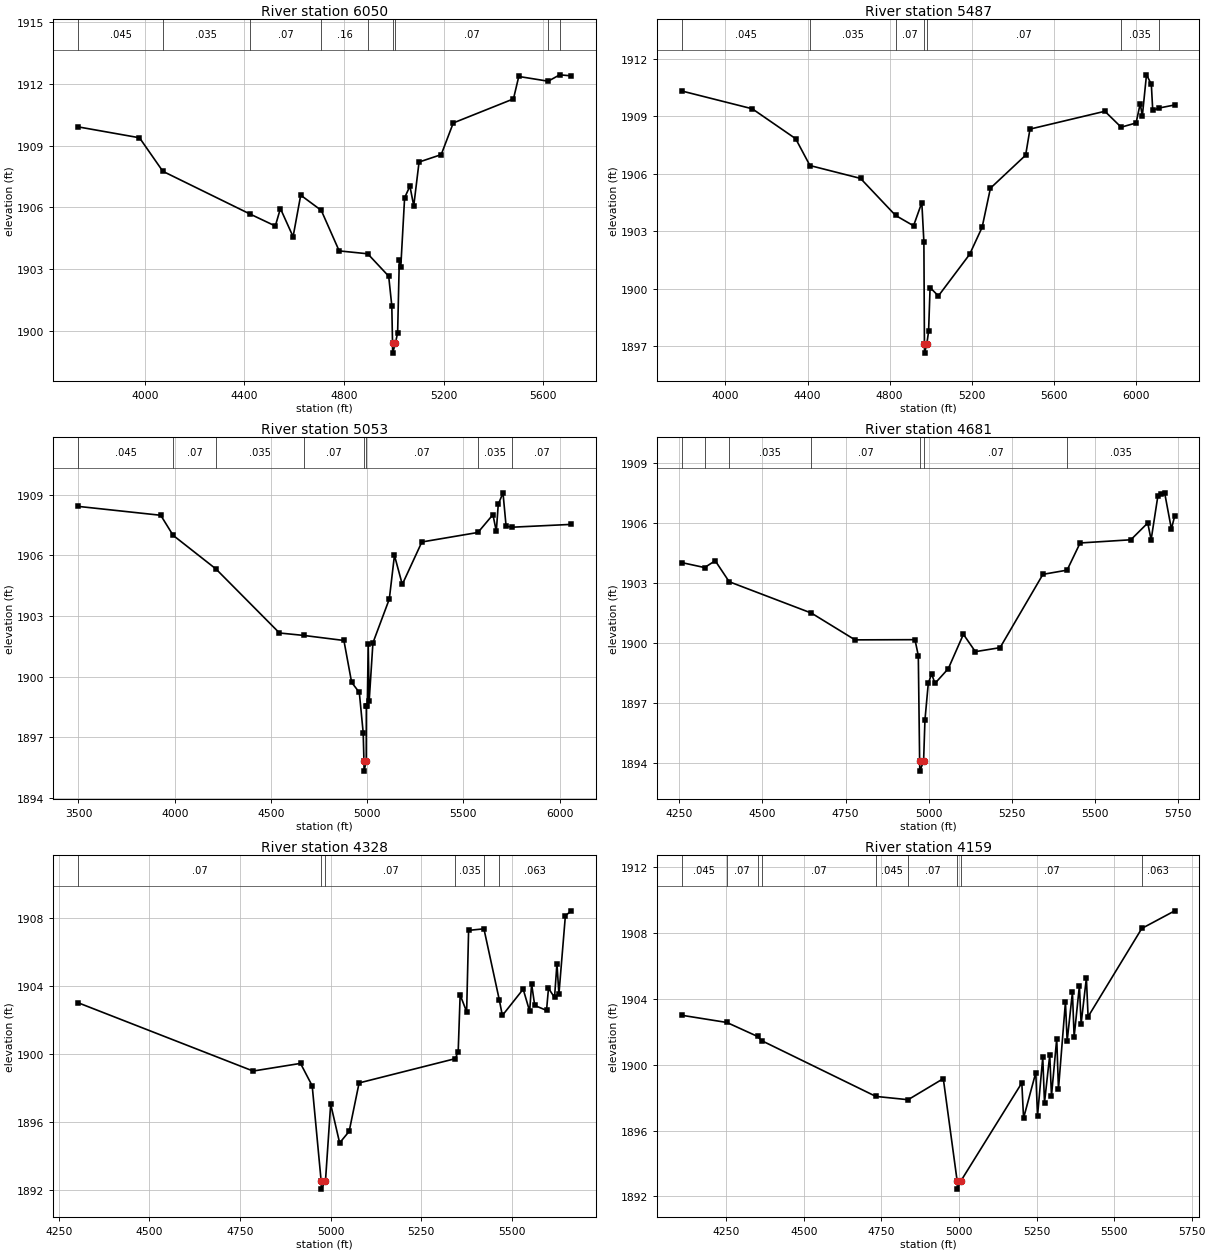
Type RM Length L Ch R = 1 ,6050    ,563,563,563
BEGIN DESCRIPTION:
Elm 01 24 6050.01
END DESCRIPTION:
XS GIS Cut Line= 3
      1536618.02      6811300.29      1537559.01      6811116.26
      1538429.08      6810582.44
#Sta/Elev= 30
  3732.2 1909.91  3978.7 1909.38  4072.4 1907.75    4421 1905.68  4523.9 1905.09
  4544.3 1905.94  4595.2 1904.57  4625.8 1906.59  4708.3 1905.85  4780.2 1903.88
  4894.7 1903.74  4978.9 1902.65  4991.4 1901.21  4994.3 1899.41  4994.8 1898.91
  5006.2 1899.41  5014.8  1899.9  5021.5 1903.42  5027.4 1903.09  5042.8 1906.46
  5064.1 1907.03  5079.5 1906.07  5100.8  1908.2  5189.7 1908.56  5238.1  1910.1
  5479.7 1911.27    5501 1912.36  5618.9 1912.13  5665.4 1912.44  5711.8 1912.39
#Mann= 9 ,-1 , 0
  3732.2    .045       0  4072.4    .035       0    4421     .07       0
  4708.3     .16       0  4894.7     .07       0  4994.3     .07       0
  5006.2     .07       0  5618.9    .035       0  5665.4     .07       0
Bank Sta=4994.3,5006.2
XS Rating Curve= 0 ,0
Exp/Cntr=0.3,0.1

Type RM Length L Ch R = 1 ,5487    ,434,434,434
BEGIN DESCRIPTION:
Elm 01 24 5487.3
END DESCRIPTION:
XS GIS Cut Line= 3
      1536413.17      6811400.98      1537607.63      6811251.68
      1538790.86      6811053.89
#Sta/Elev= 30
  3786.1 1910.31  4130.6 1909.38  4342.2 1907.82  4411.8 1906.42  4658.2 1905.75
    4829 1903.82  4916.7 1903.28    4957 1904.49  4967.1 1902.44  4969.7 1897.14
  4970.2 1896.64  4981.6 1897.14  4989.9 1897.77  4997.3 1900.06  5037.6 1899.62
    5190 1901.79  5250.8  1903.2  5291.4 1905.24  5462.9 1906.96    5484 1908.32
    5849 1909.25  5928.3 1908.42  6001.1 1908.64  6021.3 1909.65  6031.5    1909
  6051.8 1911.15  6075.4 1910.66  6082.2  1909.3  6113.8 1909.42  6189.5 1909.58
#Mann= 7 ,-1 , 0
  3786.1    .045       0  4411.8    .035       0    4829     .07       0
  4969.7     .07       0  4981.6     .07       0  5928.3    .035       0
  6113.8     .07       0
Bank Sta=4969.7,4981.6
XS Rating Curve= 0 ,0
Exp/Cntr=0.3,0.1

Type RM Length L Ch R = 1 ,5053    ,372,372,372
BEGIN DESCRIPTION:
Elm 01 24 5052.99
END DESCRIPTION:
XS GIS Cut Line= 3
      1536406.23      6811588.48      1537902.76      6811494.73
      1538947.92      6811296.81
#Sta/Elev= 30
  3497.9 1908.42  3927.5 1907.98  3991.6 1906.99  4213.9 1905.33  4544.5 1902.16
  4669.7 1902.04  4879.4 1901.79  4919.5 1899.72  4959.5 1899.22  4979.6 1897.23
  4983.6 1895.83  4984.1 1895.33  4995.5 1895.83    4996 1898.57  5001.1 1898.57
  5005.7 1901.64  5010.8  1898.8  5030.2 1901.67  5115.4 1903.84  5142.1    1906
  5182.8 1904.56  5284.6 1906.66    5576 1907.13  5653.9 1908.01  5671.4 1907.19
  5681.6 1908.52  5706.2 1909.09  5722.3 1907.44    5753 1907.39  6061.1 1907.53
#Mann= 8 ,-1 , 0
  3497.9    .045       0  3991.6     .07       0  4213.9    .035       0
  4669.7     .07       0  4983.6     .07       0  4995.5     .07       0
    5576    .035       0    5753     .07       0
Bank Sta=4983.6,4995.5
XS Rating Curve= 0 ,0
Exp/Cntr=0.3,0.1

Type RM Length L Ch R = 1 ,4681    ,353,353,353
BEGIN DESCRIPTION:
Elm 01 24 5.0
END DESCRIPTION:
XS GIS Cut Line= 3
      1537063.75      6811881.49      1537855.81      6811832.99
      1538534.92      6811706.13
#Sta/Elev= 30
  4256.5 1904.03  4325.8 1903.78  4357.9 1904.12  4399.9 1903.07  4647.5  1901.5
  4778.7 1900.16  4959.1 1900.17  4969.1 1899.37  4973.1 1894.09  4973.6 1893.59
    4985 1894.09  4989.1 1896.15  4999.1 1897.98  5009.2 1898.46  5019.2 1897.98
  5059.4 1898.72  5104.8 1900.44  5140.8 1899.57  5215.2 1899.77  5344.2 1903.44
  5416.9 1903.65  5456.1 1905.01  5608.7 1905.17  5659.6 1906.01  5669.8 1905.17
  5690.1 1907.36  5699.4 1907.45  5710.5 1907.52  5730.8 1905.71  5740.9 1906.37
#Mann= 7 ,-1 , 0
  4256.5    .035       0  4325.8     .07       0  4399.9    .035       0
  4647.5     .07       0  4973.1     .07       0    4985     .07       0
  5416.9    .035       0
Bank Sta=4973.1,4985
XS Rating Curve= 0 ,0
Exp/Cntr=0.3,0.1

Type RM Length L Ch R = 1 ,4328    ,169,169,169
BEGIN DESCRIPTION:
Elm 01 24 4404.05
END DESCRIPTION:
XS GIS Cut Line= 3
       1537121.2      6812053.87      1537883.82       6812203.9
       1538417.2      6811967.39
#Sta/Elev= 30
  4303.1    1903    4786 1898.98  4916.8 1899.43    4949 1898.11  4973.6 1892.53
  4974.1 1892.03  4985.7 1892.53    5000 1897.03  5024.7 1894.75    5051 1895.43
  5078.4 1898.28  5343.9 1899.71  5351.8 1900.13  5357.2 1903.46  5375.1 1902.47
  5380.5 1907.26  5422.8 1907.35  5465.2 1903.17  5473.6 1902.25  5531.1  1903.8
  5548.9  1902.5  5554.4  1904.1  5562.9 1902.84  5595.5 1902.55  5600.9 1903.85
  5617.6 1903.31  5624.2  1905.3  5629.7 1903.51  5647.5 1908.12  5663.8 1908.41
#Mann= 6 ,-1 , 0
  4303.1     .07       0  4973.6     .07       0  4985.7     .07       0
  5343.9    .035       0  5422.8     .07       0  5465.2    .063       0
Bank Sta=4973.6,4985.7
XS Rating Curve= 0 ,0
Exp/Cntr=0.3,0.1

Type RM Length L Ch R = 1 ,4159    ,185,185,185
BEGIN DESCRIPTION:
Elm 01 24 4170.03
END DESCRIPTION:
XS GIS Cut Line= 4
      1536863.55       6812299.7       1537681.3      6812354.63
      1537949.64      6812306.91      1538396.47      6812088.03
#Sta/Elev= 30
  4105.8    1903    4252 1902.56    4351 1901.71  4363.6 1901.46  4732.2 1898.07
  4836.1 1897.87  4949.5 1899.15  4994.1 1892.94  4994.6 1892.44  5006.3 1892.94
  5202.6 1898.89  5208.2 1896.75  5247.6 1899.52  5253.2 1896.89  5270.1 1900.44
  5275.7 1897.69  5292.6 1900.58  5298.2 1898.11  5315.1 1901.58  5320.7 1898.51
  5343.2 1903.81  5348.7 1901.43  5365.7 1904.39  5371.2 1901.69  5388.2 1904.79
  5393.7 1902.48  5410.7 1905.26  5416.2 1902.91  5589.3 1908.27  5695.5 1909.34
#Mann= 9 ,-1 , 0
  4105.8    .045       0    4252     .07       0    4351    .045       0
  4363.6     .07       0  4732.2    .045       0  4836.1     .07       0
  4994.1     .07       0  5006.3     .07       0  5589.3    .063       0
Bank Sta=4994.1,5006.3
XS Rating Curve= 0 ,0
Exp/Cntr=0.3,0.1

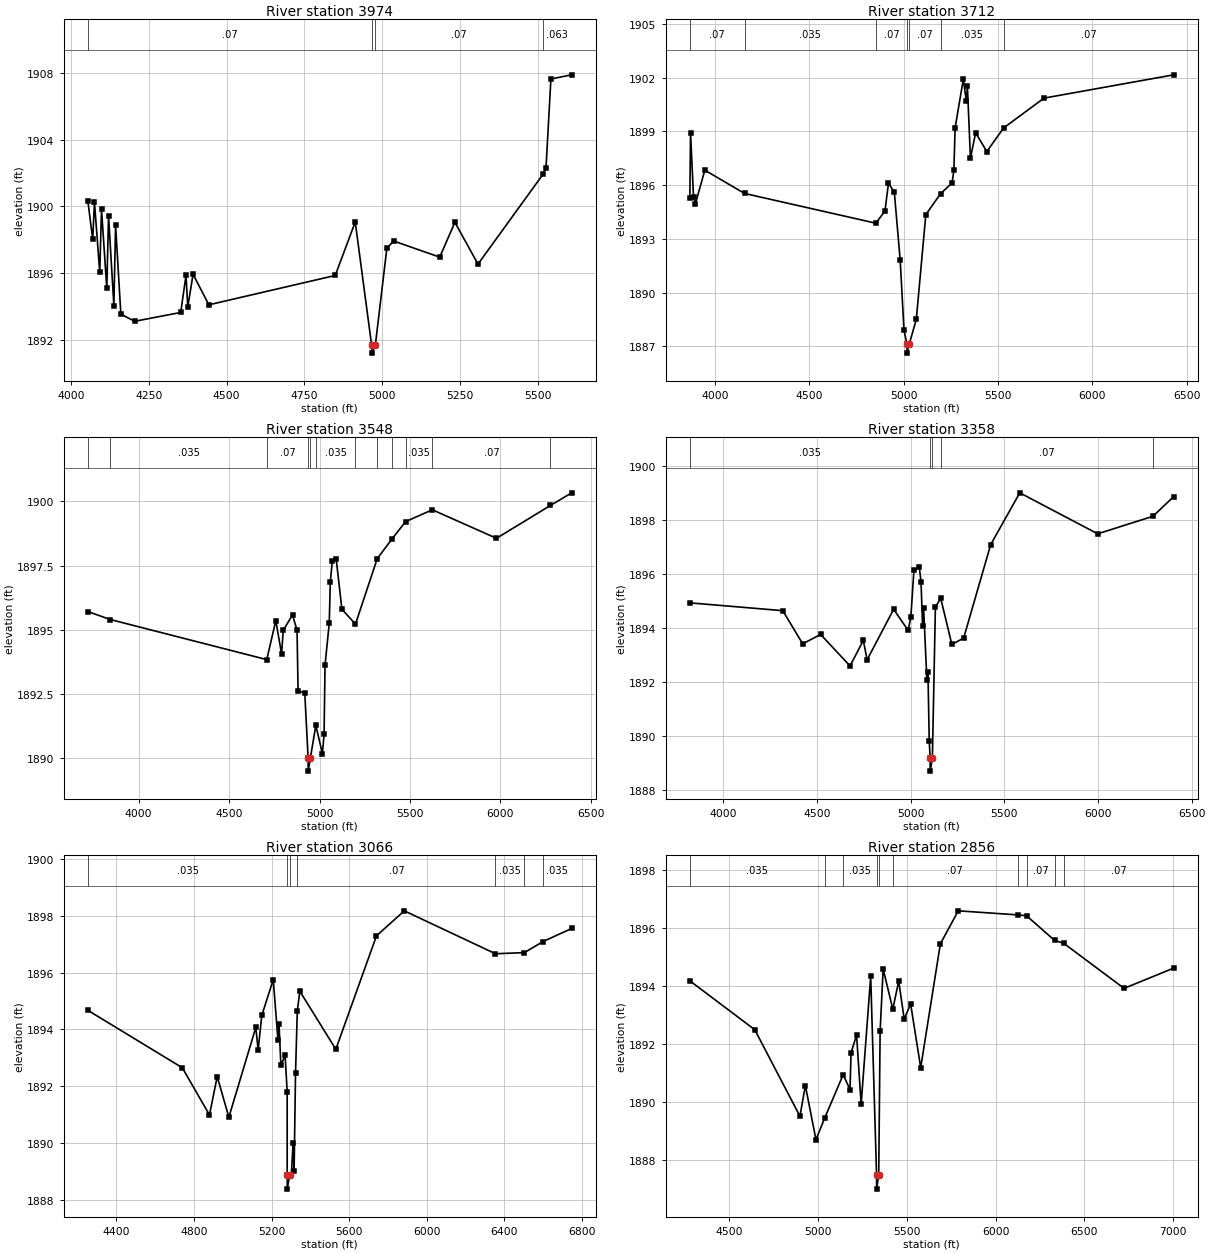
Type RM Length L Ch R = 1 ,3974    ,262,262,262
BEGIN DESCRIPTION:
Elm 01 24 3947.31
END DESCRIPTION:
XS GIS Cut Line= 3
      1537009.64      6812911.57      1537712.85      6812572.37
      1538377.86      6812179.17
#Sta/Elev= 30
  4054.6 1900.33  4070.2 1898.02  4075.8 1900.25  4092.8 1896.05  4098.4 1899.83
  4115.4 1895.08    4121 1899.44  4138.1 1894.04  4143.6 1898.87  4160.5 1893.54
  4204.9 1893.11  4352.7 1893.64  4369.7 1895.87  4375.3 1893.96  4392.3 1895.93
  4443.1  1894.1  4848.7 1895.86    4913 1899.07  4965.4  1891.7  4965.9  1891.2
  4977.6  1891.7  5014.4 1897.48  5035.9 1897.93  5184.2 1896.96  5232.9 1899.05
    5307 1896.54  5515.7 1901.93  5525.4 1902.32  5541.1 1907.65  5607.9  1907.9
#Mann= 4 ,-1 , 0
  4054.6     .07       0  4965.4     .07       0  4977.6     .07       0
  5515.7    .063       0
Bank Sta=4965.4,4977.6
XS Rating Curve= 0 ,0
Exp/Cntr=0.3,0.1

Type RM Length L Ch R = 1 ,3712    ,164,164,164
BEGIN DESCRIPTION:
Elm 01 24 3712.16
END DESCRIPTION:
XS GIS Cut Line= 3
      1536876.25      6812993.85       1537968.3      6812708.27
      1539223.55      6812010.34
#Sta/Elev= 30
  3866.3 1895.31  3869.9 1898.92  3885.7 1895.35    3896 1894.97  3945.6 1896.84
  4156.2 1895.54  4852.2 1893.88  4900.6 1894.56  4919.3 1896.12  4950.3  1895.6
  4981.4 1891.81  5001.5 1887.91  5017.1 1887.13  5017.6 1886.63  5029.3 1887.13
  5066.7 1888.51  5117.2 1894.36  5195.7 1895.53  5256.5 1896.13  5265.9 1896.83
  5272.5  1899.2    5316 1901.91    5332 1900.68  5337.7 1901.51  5353.7 1897.51
  5381.2 1898.92  5440.7 1897.88  5529.1 1899.19  5743.7 1900.86  6431.3 1902.16
#Mann= 7 ,-1 , 0
  3866.3     .07       0  4156.2    .035       0  4852.2     .07       0
  5017.1     .07       0  5029.3     .07       0  5195.7    .035       0
  5529.1     .07       0
Bank Sta=5017.1,5029.3
XS Rating Curve= 0 ,0
Exp/Cntr=0.3,0.1

Type RM Length L Ch R = 1 ,3548    ,190,190,190
BEGIN DESCRIPTION:
Elm 01 24 3548.37
END DESCRIPTION:
XS GIS Cut Line= 3
      1536872.53      6813043.24      1538119.34      6812755.15
      1539395.35      6812190.06
#Sta/Elev= 30
    3719 1895.71  3842.9  1895.4  4708.2 1893.84  4758.1 1895.36  4790.1 1894.06
  4799.2 1894.98  4850.5 1895.58  4875.6 1894.98  4881.3 1892.61  4918.3 1892.55
  4936.8    1890  4937.3  1889.5    4949    1890  4979.4 1891.28  5015.8 1890.18
    5025 1890.93  5030.4 1893.63  5053.7 1895.26  5059.5 1896.87  5070.5 1897.67
  5092.3 1897.74  5123.6  1895.8  5198.6 1895.22    5319 1897.77    5401 1898.54
    5476 1899.21  5623.5 1899.67  5978.2 1898.56  6276.8 1899.84  6394.2 1900.33
#Mann= 12 ,-1 , 0
    3719     .07       0  3842.9    .035       0  4708.2     .07       0
  4936.8    .035       0    4949     .07       0  4979.4    .035       0
  5198.6     .07       0    5319    .035       0    5401     .07       0
    5476    .035       0  5623.5     .07       0  6276.8    .035       0
Bank Sta=4936.8,4949
XS Rating Curve= 0 ,0
Exp/Cntr=0.3,0.1

Type RM Length L Ch R = 1 ,3358    ,292,292,292
BEGIN DESCRIPTION:
Elm 01 24 3358.35
END DESCRIPTION:
XS GIS Cut Line= 3
      1536939.34       6813096.9      1538101.12      6812921.82
      1539384.96      6812343.69
#Sta/Elev= 30
  3821.3 1894.94  4317.4 1894.65  4423.7 1893.42  4519.1 1893.77  4676.5  1892.6
  4747.3 1893.55  4767.5 1892.83  4909.1  1894.7  4986.6 1893.92  5001.1 1894.42
  5017.3 1896.14  5045.9 1896.27  5055.3 1895.72  5063.6 1894.08  5069.1 1894.74
  5086.7 1892.07  5092.2 1892.38  5099.2 1889.82  5103.8  1889.2  5104.3  1888.7
    5116  1889.2  5132.1 1894.78  5160.4 1895.11  5219.8  1893.4  5282.8 1893.63
  5427.2  1897.1  5582.5 1899.02  5998.5  1897.5  6293.2 1898.15  6404.2 1898.88
#Mann= 5 ,-1 , 0
  3821.3    .035       0  5103.8    .035       0    5116    .035       0
  5160.4     .07       0  6293.2    .035       0
Bank Sta=5103.8,5116
XS Rating Curve= 0 ,0
Exp/Cntr=0.3,0.1

Type RM Length L Ch R = 1 ,3066    ,210,210,210
BEGIN DESCRIPTION:
Elm 01 24 3066.04
END DESCRIPTION:
XS GIS Cut Line= 3
      1537158.38      6813093.69      1537900.59      6813111.92
      1539525.62      6812458.27
#Sta/Elev= 30
  4252.8 1894.67  4739.6 1892.65  4879.6 1890.99  4919.6 1892.34  4979.6 1890.91
  5118.6 1894.07  5130.5 1893.27  5149.3 1894.49  5208.4 1895.75  5232.6 1893.63
    5238 1894.18  5247.9 1892.73  5269.5 1893.09  5280.2  1891.8  5280.3 1888.88
  5280.8 1888.38  5292.5 1888.88  5301.8 1888.89  5310.5 1889.99  5315.9 1889.02
  5323.3 1892.48  5332.4 1894.65  5345.5 1895.34  5530.9  1893.3  5740.5 1897.29
  5883.8 1898.17  6353.9 1896.66  6502.8  1896.7  6599.3 1897.09  6746.8 1897.55
#Mann= 7 ,-1 , 0
  4252.8    .035       0  5280.3    .035       0  5292.5    .035       0
  5332.4     .07       0  6353.9    .035       0  6502.8     .07       0
  6599.3    .035       0
Bank Sta=5280.3,5292.5
XS Rating Curve= 0 ,0
Exp/Cntr=0.3,0.1

Type RM Length L Ch R = 1 ,2856    ,160,160,160
BEGIN DESCRIPTION:
Elm 01 24 2856.24
END DESCRIPTION:
XS GIS Cut Line= 3
      1537145.34      6813174.41      1537856.32      6813304.63
      1539744.34      6812640.57
#Sta/Elev= 30
  4278.9 1894.18  4644.5 1892.49  4898.7  1889.5  4929.2 1890.56  4988.9 1888.69
  5037.7 1889.43  5142.3 1890.94  5180.5 1890.42  5186.6  1891.7  5217.6  1892.3
  5243.3 1889.92  5297.1 1894.33  5330.1 1887.48  5330.6 1886.98  5342.3 1887.48
  5350.1 1892.43  5367.2 1894.59  5421.6  1893.2  5454.8 1894.17  5485.7 1892.86
    5522 1893.38  5578.6 1891.18  5689.3 1895.46  5790.1  1896.6  6124.2 1896.46
  6174.3 1896.43  6332.1 1895.58  6383.3 1895.48  6723.7 1893.92  7003.1 1894.62
#Mann= 10 ,-1 , 0
  4278.9    .035       0  5037.7     .07       0  5142.3    .035       0
  5330.1    .035       0  5342.3    .035       0  5421.6     .07       0
  6124.2    .035       0  6174.3     .07       0  6332.1    .035       0
  6383.3     .07       0
Bank Sta=5330.1,5342.3
XS Rating Curve= 0 ,0
Exp/Cntr=0.3,0.1

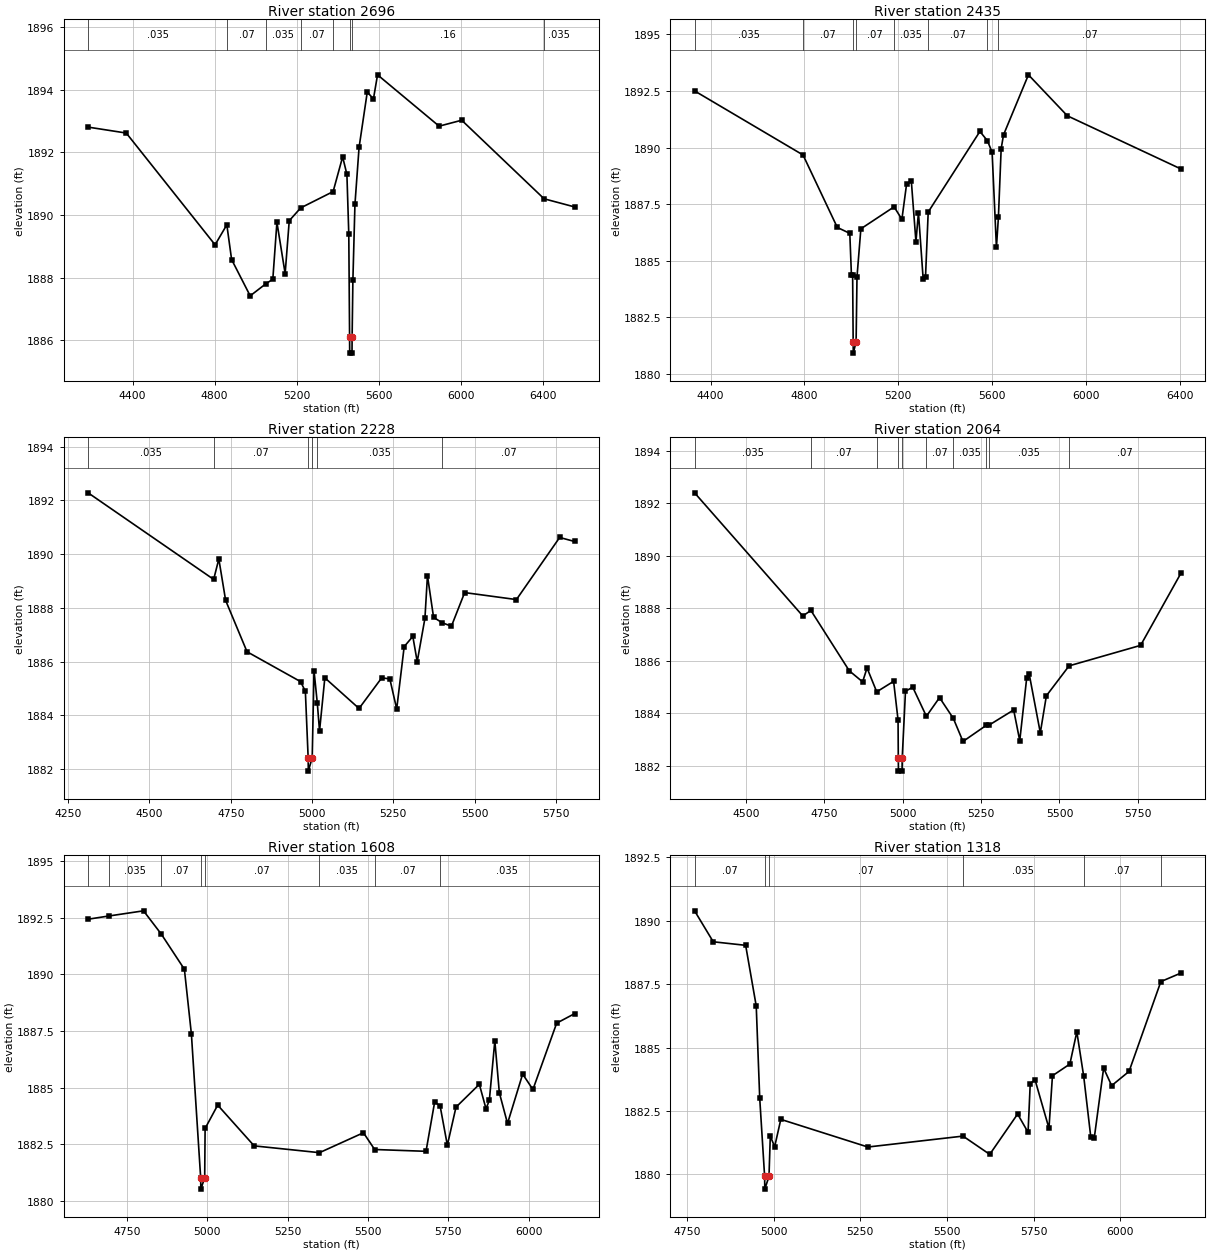
Type RM Length L Ch R = 1 ,2696    ,261,261,261
BEGIN DESCRIPTION:
Elm 01 24 2695.82
END DESCRIPTION:
XS GIS Cut Line= 3
      1537080.26       6813351.5      1537900.59      6813450.46
       1539444.9      6813531.19
#Sta/Elev= 30
    4183 1892.81  4369.1 1892.62  4802.2 1889.05  4859.5 1889.69  4882.8 1888.58
  4973.4 1887.42  5050.8 1887.81  5083.8 1887.95  5103.8 1889.77  5143.9 1888.13
  5163.9 1889.82  5219.9 1890.23  5377.9 1890.75  5424.3 1891.86  5445.1  1891.3
  5454.3  1889.4  5458.2 1886.09  5458.7 1885.59    5470 1885.59  5470.5 1886.09
  5474.3 1887.92  5484.3 1890.34  5504.4 1892.16  5544.4 1893.93  5574.5 1893.71
  5594.5 1894.48  5894.9 1892.84    6005 1893.03  6406.8 1890.52  6555.7 1890.26
#Mann= 8 ,-1 , 0
    4183    .035       0  4859.5     .07       0  5050.8    .035       0
  5219.9     .07       0  5377.9     .16       0  5458.2     .07       0
  5470.5     .16       0  6406.8    .035       0
Bank Sta=5458.2,5470.5
XS Rating Curve= 0 ,0
Exp/Cntr=0.3,0.1

Type RM Length L Ch R = 1 ,2435    ,207,207,207
BEGIN DESCRIPTION:
Elm 01 24 2434.71
END DESCRIPTION:
XS GIS Cut Line= 3
      1537082.86      6813408.79      1537713.09      6813637.96
      1539106.28      6813815.04
#Sta/Elev= 30
  4331.6  1892.5  4794.2 1889.67  4940.4 1886.47  4993.6 1886.21  5000.6 1884.36
  5005.7 1884.36    5008 1881.42  5008.5 1880.92  5020.5 1881.42  5024.3 1884.29
  5040.8 1886.41  5182.5 1887.38  5215.8 1886.83    5236  1888.4  5256.1 1888.51
  5275.7 1885.84  5286.4 1887.13  5306.5  1884.2  5316.6  1884.3    5328 1887.15
  5548.5 1890.71  5580.6  1890.3  5600.6 1889.79    5619 1885.59  5627.4 1886.91
  5639.2 1889.95  5649.3 1890.56  5755.5 1893.21  5921.5  1891.4  6406.6 1889.05
#Mann= 8 ,-1 , 0
  4331.6    .035       0  4794.2     .07       0    5008     .07       0
  5020.5     .07       0  5182.5    .035       0    5328     .07       0
  5580.6     .16       0  5627.4     .07       0
Bank Sta=5008,5020.5
XS Rating Curve= 0 ,0
Exp/Cntr=0.3,0.1

Type RM Length L Ch R = 1 ,2228    ,164,164,164
BEGIN DESCRIPTION:
Elm 01 24 2228.4
END DESCRIPTION:
XS GIS Cut Line= 3
      1537060.55      6813424.43      1537637.79      6813819.39
      1538395.19      6814066.79
#Sta/Elev= 30
  4311.5 1892.28  4697.6 1889.06  4713.5 1889.82  4734.4 1888.28  4800.2 1886.37
  4964.7 1885.26  4979.6  1884.9  4988.2 1882.43  4988.7 1881.93  5000.7 1882.43
  5006.2 1885.67  5016.4 1884.45  5023.2 1883.42  5039.5  1885.4  5144.7 1884.26
  5214.5  1885.4  5239.4 1885.36  5260.5 1884.24  5283.5 1886.56  5310.1 1886.94
  5323.6    1886  5347.3 1887.61  5355.1  1889.2  5373.9 1887.65    5400 1887.45
  5428.8 1887.32  5469.5 1888.57  5628.7 1888.31  5761.7 1890.62  5807.7 1890.47
#Mann= 6 ,-1 , 0
  4311.5    .035       0  4697.6     .07       0  4988.2     .07       0
  5000.7     .07       0  5016.4    .035       0    5400     .07       0
Bank Sta=4988.2,5000.7
XS Rating Curve= 0 ,0
Exp/Cntr=0.3,0.1

Type RM Length L Ch R = 1 ,2064    ,456,456,456
BEGIN DESCRIPTION:
Elm 01 24 2064.3
END DESCRIPTION:
XS GIS Cut Line= 3
      1537023.61       6813430.9      1537492.39      6813897.51
      1538325.76      6814214.36
#Sta/Elev= 30
  4335.3  1892.4  4680.7 1887.71  4706.6 1887.92  4829.2 1885.62  4871.7  1885.2
  4885.8 1885.73  4916.7 1884.82  4970.6 1885.22  4984.8 1883.75  4985.6  1882.3
  4986.1  1881.8  4997.6  1881.8  4998.1  1882.3  5008.5 1884.84  5031.6    1885
  5075.2 1883.89  5117.2  1884.6  5161.2 1883.81  5192.1 1882.93  5265.9 1883.54
  5276.3 1883.56  5353.9 1884.13  5373.3 1882.96  5395.4 1885.34  5403.4  1885.5
  5438.9 1883.26  5458.3 1884.67  5530.8 1885.81  5759.1 1886.59  5888.3 1889.35
#Mann= 10 ,-1 , 0
  4335.3    .035       0  4706.6     .07       0  4916.7    .035       0
  4985.6    .035       0  4998.1    .035       0  5075.2     .07       0
  5161.2    .035       0  5265.9     .07       0  5276.3    .035       0
  5530.8     .07       0
Bank Sta=4985.6,4998.1
XS Rating Curve= 0 ,0
Exp/Cntr=0.3,0.1

Type RM Length L Ch R = 1 ,1608    ,290,290,290
BEGIN DESCRIPTION:
Elm 01 24 1608.091
END DESCRIPTION:
XS GIS Cut Line= 3
      1536869.57      6813749.95      1537148.78      6813994.41
      1538250.94      6814298.71
#Sta/Elev= 30
  4628.9 1892.44  4692.6 1892.58  4801.4 1892.81  4856.8 1891.78  4928.6 1890.23
  4950.4 1887.37  4979.3 1881.02  4979.8 1880.52  4991.8 1881.02  4993.1  1883.2
  5032.3 1884.23  5145.8 1882.43  5349.1 1882.13    5486 1883.01  5520.9 1882.27
  5680.8 1882.19  5707.7 1884.37  5724.7 1884.19  5747.2 1882.46  5774.1 1884.14
  5846.8 1885.15  5867.5 1884.07  5877.9 1884.44    5895 1887.07    5909 1884.78
  5934.5 1883.42  5981.6  1885.6  6013.6 1884.92  6087.5 1887.85  6143.4 1888.27
#Mann= 8 ,-1 , 0
  4628.9     .07       0  4692.6    .035       0  4856.8     .07       0
  4979.3     .07       0  4991.8     .07       0  5349.1    .035       0
  5520.9     .07       0  5724.7    .035       0
Bank Sta=4979.3,4991.8
XS Rating Curve= 0 ,0
Exp/Cntr=0.3,0.1

Type RM Length L Ch R = 1 ,1318    ,302,302,302
BEGIN DESCRIPTION:
Elm 01 24 1318.45
END DESCRIPTION:
XS GIS Cut Line= 3
      1536829.99        6814213.      1537054.52      6814253.16
       1538224.4      6814363.86
#Sta/Elev= 30
  4771.9 1890.39  4825.7 1889.17  4919.2 1889.03  4949.7 1886.64  4959.8    1883
  4973.9 1879.92  4974.4 1879.42  4986.5 1879.92  4990.3 1881.51  5002.8 1881.09
  5020.6 1882.17  5271.7 1881.08  5546.1 1881.51  5623.2 1880.79  5703.6 1882.38
  5733.7 1881.66    5740 1883.58  5753.8 1883.73    5794 1881.82  5804.1 1883.89
  5854.3 1884.35  5874.4 1885.62  5894.2 1883.87  5914.5 1881.49  5924.6 1881.43
  5951.7 1884.19  5974.8  1883.5    6025 1884.06  6116.7  1887.6  6175.1 1887.94
#Mann= 6 ,-1 , 0
  4771.9     .07       0  4973.9     .07       0  4986.5     .07       0
  5546.1    .035       0  5894.2     .07       0  6116.7    .035       0
Bank Sta=4973.9,4986.5
XS Rating Curve= 0 ,0
Exp/Cntr=0.3,0.1