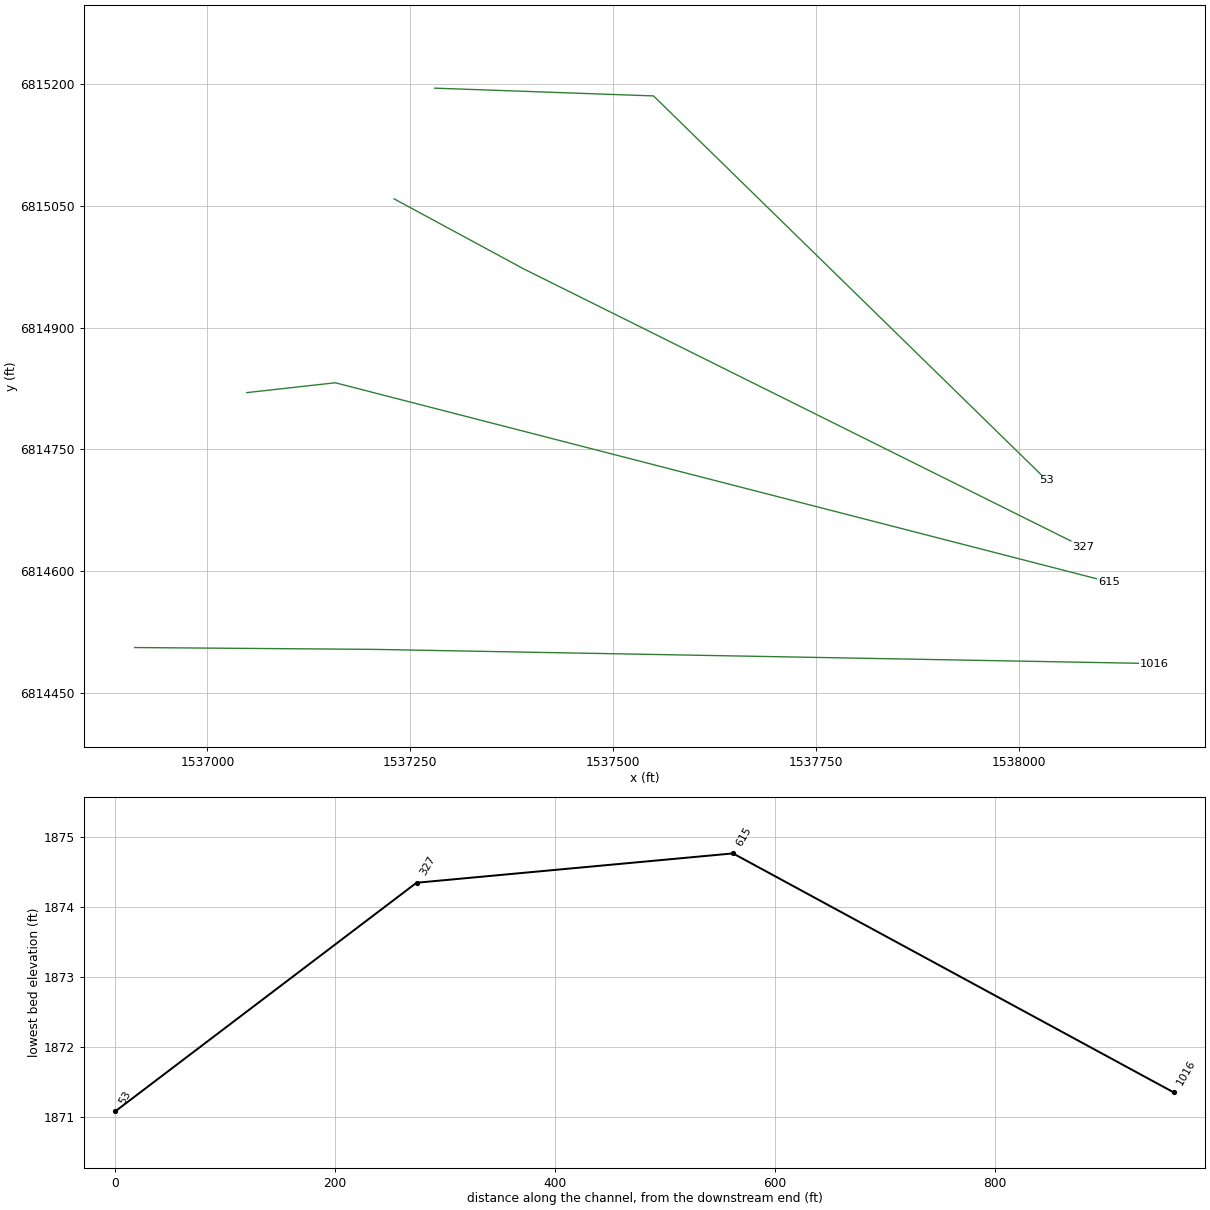
HEC-RAS study Elm 01 24.prj: Elm 01 24 Base Level Engineering

--- Elm 01 24.g01 (geometry) --- (continued)

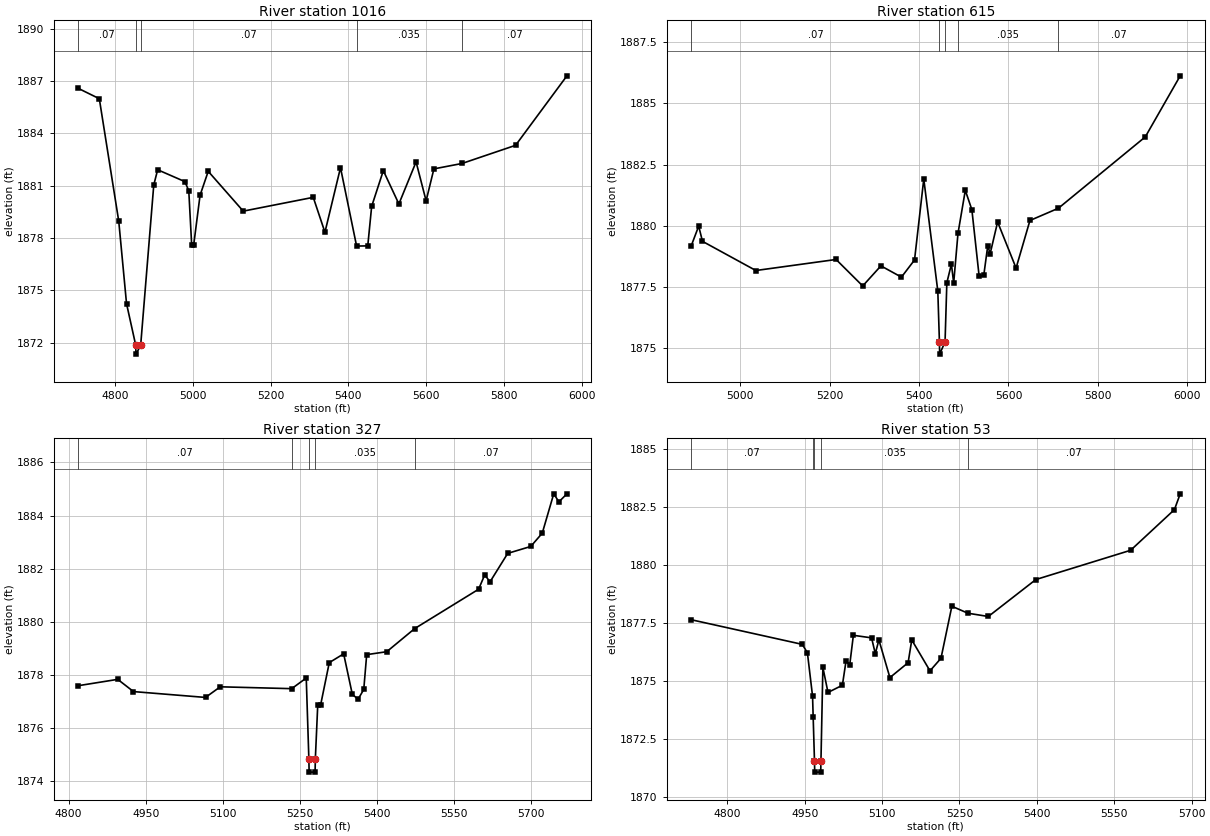
Type RM Length L Ch R = 1 ,1016    ,401,401,401
BEGIN DESCRIPTION:
Elm 01 24 1016.178
END DESCRIPTION:
XS GIS Cut Line= 3
      1536910.23      6814505.69      1537205.12      6814503.42
      1538166.96      6814485.94
#Sta/Elev= 30
  4705.1 1886.58  4759.9 1885.98  4809.9 1878.96  4829.9 1874.24  4853.6 1871.85
  4854.1 1871.35  4866.2 1871.85  4899.9 1881.04  4909.9 1881.91  4979.9 1881.23
  4989.9 1880.71  4997.4 1877.58  5002.4 1877.58  5018.9 1880.45  5039.9 1881.82
  5129.9 1879.54  5309.9 1880.33  5339.9 1878.33  5379.9 1882.03  5421.3 1877.54
    5450 1877.55    5460 1879.81    5490 1881.86    5530 1879.95  5574.2 1882.36
    5600 1880.13    5620 1881.96  5692.3 1882.27    5830 1883.31    5962 1887.29
#Mann= 5 ,-1 , 0
  4705.1     .07       0  4853.6     .07       0  4866.2     .07       0
  5421.3    .035       0  5692.3     .07       0
Bank Sta=4853.6,4866.2
XS Rating Curve= 0 ,0
Exp/Cntr=0.3,0.1

Type RM Length L Ch R = 1 ,615     ,288,288,288
BEGIN DESCRIPTION:
Elm 01 24 615.412
END DESCRIPTION:
XS GIS Cut Line= 3
      1537048.46      6814819.85      1537157.49      6814831.98
      1538110.62      6814586.64
#Sta/Elev= 30
  4890.3 1879.19  4906.9 1879.99  4915.4 1879.37  5034.8 1878.18  5214.3 1878.63
  5273.9 1877.55  5314.6 1878.37  5360.5 1877.91  5389.8 1878.61  5410.5 1881.91
  5441.9 1877.34  5445.5 1875.27    5446 1874.77  5458.1 1875.27  5462.1 1877.68
  5472.3 1878.44  5477.4 1877.67    5487 1879.69  5503.4 1881.45  5518.1 1880.66
  5534.4 1877.94  5544.7 1877.98  5553.7  1879.2  5558.9 1878.86  5575.7 1880.16
    5617 1878.28    5648 1880.22  5711.7 1880.72  5906.1 1883.63  5984.2 1886.12
#Mann= 5 ,-1 , 0
  4890.3     .07       0  5445.5     .07       0  5458.1     .07       0
    5487    .035       0  5711.7     .07       0
Bank Sta=5445.5,5458.1
XS Rating Curve= 0 ,0
Exp/Cntr=0.3,0.1

Type RM Length L Ch R = 1 ,327     ,274,274,274
BEGIN DESCRIPTION:
Elm 01 24 326.578
END DESCRIPTION:
XS GIS Cut Line= 3
      1537229.99      6815058.63      1537389.74      6814972.27
      1538078.94      6814629.58
#Sta/Elev= 30
  4818.4  1877.6  4895.7 1877.84  4926.4 1877.38  5066.5 1877.16  5095.2 1877.56
  5234.2 1877.49  5262.5 1877.89  5267.6 1874.85  5268.1 1874.35  5279.7 1874.35
  5280.2 1874.85  5284.9 1876.89  5290.5 1876.88  5307.3 1878.47  5335.3  1878.8
  5352.1 1877.28  5363.3 1877.09  5374.4 1877.46  5380.1 1878.77  5419.1 1878.88
  5473.5 1879.75  5597.8 1881.23  5609.7 1881.77  5620.1 1881.51  5654.5 1882.58
  5699.3 1882.84  5721.7 1883.34    5744 1884.82  5754.1 1884.52  5769.7 1884.82
#Mann= 5 ,-1 , 0
  4818.4     .07       0  5234.2    .035       0  5267.6     .07       0
  5280.2    .035       0  5473.5     .07       0
Bank Sta=5267.6,5280.2
XS Rating Curve= 0 ,0
Exp/Cntr=0.3,0.1

Type RM Length L Ch R = 1 ,53      ,0,0,0
BEGIN DESCRIPTION:
Elm 01 24 53.201
END DESCRIPTION:
XS GIS Cut Line= 3
      1537280.04      6815195.06      1537549.67      6815185.49
       1538034.5      6814711.69
#Sta/Elev= 30
  4730.2 1877.64  4945.3 1876.58  4955.3 1876.22  4965.3 1874.35  4966.5 1873.45
    4969 1871.58  4969.5 1871.08  4981.1 1871.08  4981.6 1871.58  4985.3 1875.59
  4995.2 1874.51  5023.1 1874.82  5030.3 1875.88  5037.3 1875.69  5044.4 1876.97
  5079.7 1876.86  5086.9 1876.18  5093.9 1876.77  5115.2 1875.15  5150.5 1875.79
  5157.6 1876.77  5192.9 1875.44  5214.2 1875.98  5235.3 1878.22  5266.5 1877.92
    5306 1877.78  5398.1 1879.37  5581.8 1880.63  5666.7 1882.38  5677.9 1883.06
#Mann= 5 ,-1 , 0
  4730.2     .07       0  4966.5    .035       0    4969    .035       0
  4981.6    .035       0  5266.5     .07       0
Bank Sta=4969,4981.6
XS Rating Curve= 0 ,0
Exp/Cntr=0.3,0.1

Chan Stop Cuts=-1
Use User Specified Reach Order=0
Composite Channel Slope=5