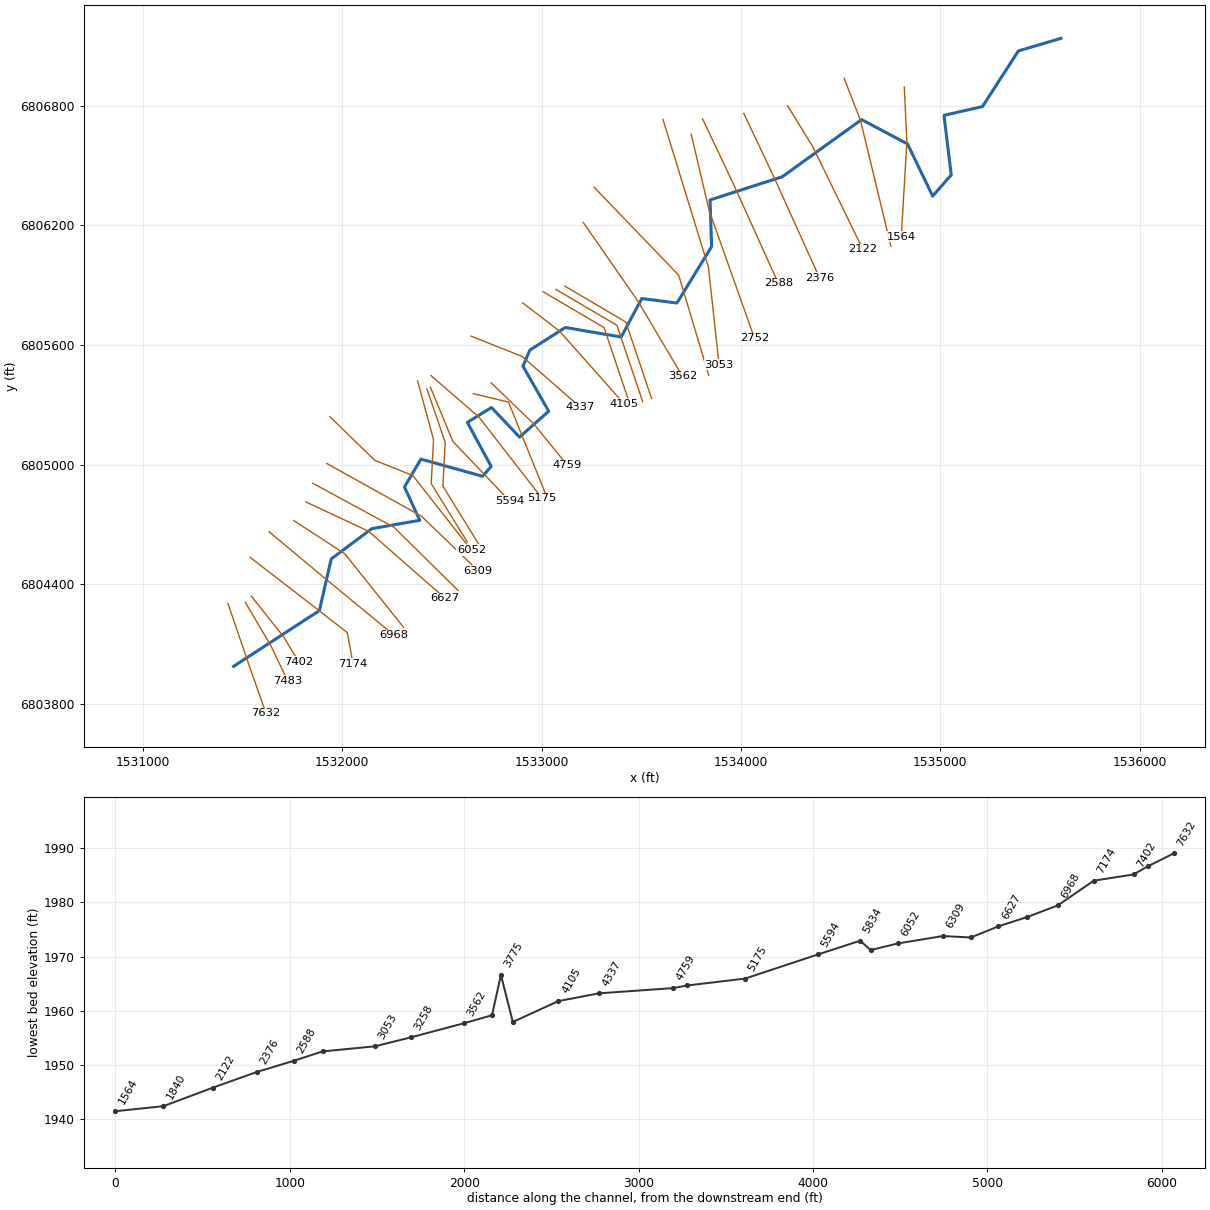
--- Elm 01 25.prj (project) ---

Proj Title=Elm 01 25 Base Level Engineering
Current Plan=p01
Default Exp/Contr=0.3,0.1
English Units
Geom File=g01
Flow File=f01
Plan File=p01
BEGIN DESCRIPTION:
Elm 01 25
END DESCRIPTION:

--- Elm 01 25.p01 (plan) ---

Plan Title=Multiple Run
Short Identifier=Multiple
Geom File=g01
Flow File=f01
Subcritical Flow
K Sum by GR= 0
Std Step Tol= 0.01
Critical Tol= 0.01
Num of Std Step Trials= 20
Max Error Tol= 0.3
Flow Tol Ratio= 0.001
Split Flow NTrial= 30
Split Flow Tol= 0.02
Split Flow Ratio= 0.02
Log Output Level= 0
Friction Slope Method= 1
Unsteady Friction Slope Method= 2
Unsteady Bridges Friction Slope Method= 1
Parabolic Critical Depth
Global Vel Dist=  1 , 1 , 1
Global Log Level= 0
CheckData=True
Encroach Param= -1, 0, 0, 0
BEGIN DESCRIPTION:
Multiple Run
END DESCRIPTION:

--- Elm 01 25.f01 (steady flow) ---

Flow Title=Multiple
Number of Profiles=7
Profile Names=10-year,25-year,50-year,1pct_min,100-year,1pct_plu,500-year
River Rch & RM= Elm 01 25,Reach-1,7632
     165     226     276     210     337     463     506
River Rch & RM= Elm 01 25,Reach-1,7174
     369     528     665     520     833    1150    1320
River Rch & RM= Elm 01 25,Reach-1,3258
     379     543     684     534     856    1180    1360
Boundary for River Rch & Prof#=Elm 01 25,Reach-1,1
Up Type=0
Dn Type=3
Dn Slope=0.005
Boundary for River Rch & Prof#=Elm 01 25,Reach-1,2
Up Type=0
Dn Type=3
Dn Slope=0.005
Boundary for River Rch & Prof#=Elm 01 25,Reach-1,3
Up Type=0
Dn Type=3
Dn Slope=0.005
Boundary for River Rch & Prof#=Elm 01 25,Reach-1,4
Up Type=0
Dn Type=3
Dn Slope=0.005
Boundary for River Rch & Prof#=Elm 01 25,Reach-1,5
Up Type=0
Dn Type=3
Dn Slope=0.005
Boundary for River Rch & Prof#=Elm 01 25,Reach-1,6
Up Type=0
Dn Type=3
Dn Slope=0.005
Boundary for River Rch & Prof#=Elm 01 25,Reach-1,7
Up Type=0
Dn Type=3
Dn Slope=0.005

--- Elm 01 25.g01 (geometry) ---

Geom Title=Existing Conditions

River Reach=Elm 01 25,Reach-1
Reach XY= 30
      1531455.00      6803988.00      1531885.70      6804267.97
      1531945.00      6804527.35      1532148.33      6804678.70
      1532388.98      6804720.87      1532312.30      6804887.92
      1532394.89      6805027.70      1532703.98      6804941.45
      1532747.25      6804991.02      1532627.60      6805211.66
      1532748.78      6805286.57      1532889.58      6805137.87
      1533035.72      6805267.97      1532906.69      6805493.68
      1532941.29      6805574.51      1533119.04      6805687.90
      1533399.35      6805639.97      1533502.42      6805833.03
      1533678.84      6805810.56      1533852.74      6806093.56
      1533844.88      6806327.37      1534207.30      6806443.83
      1534604.99      6806730.47      1534835.39      6806608.20
      1534961.53      6806346.88      1535054.63      6806453.15
      1535018.16      6806751.73      1535211.21      6806795.81
      1535391.33      6807074.77      1535605.00      6807138.00

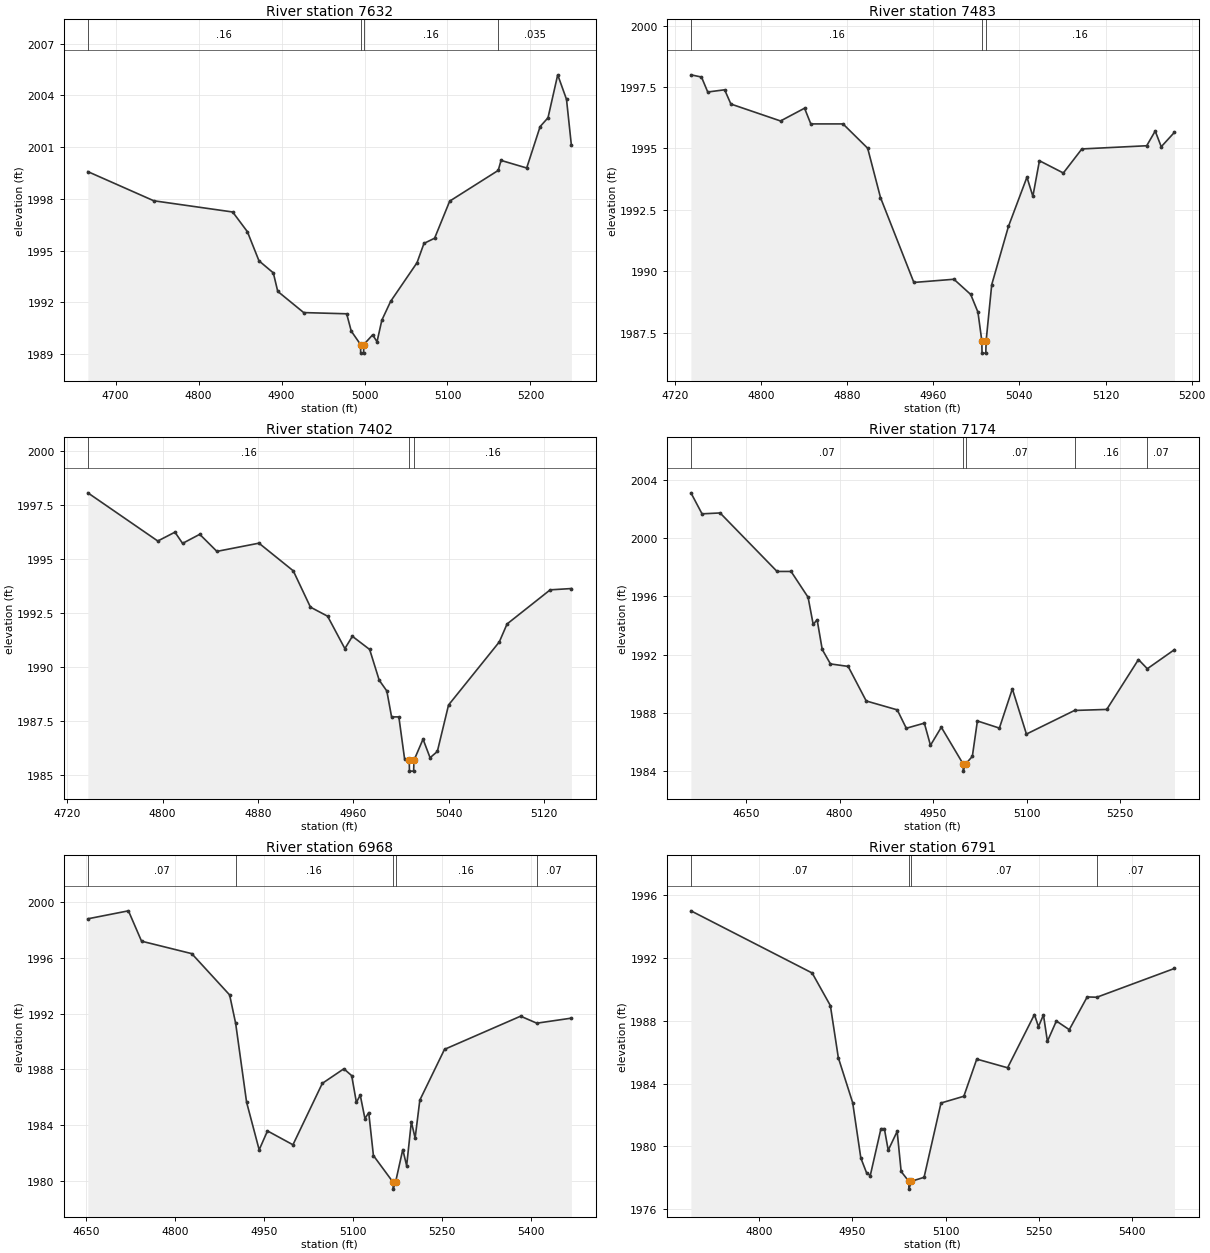
Type RM Length L Ch R = 1,7632,149,149,149
BEGIN DESCRIPTION:
Elm 01 25 7631.829
END DESCRIPTION:
XS GIS Cut Line= 3
      1531427.17      6804303.21      1531535.14      6803987.67
      1531617.99      6803752.44
#Sta/Elev= 30
  4666.5 1999.58  4746.0 1997.89  4841.1 1997.24  4858.8 1996.10  4872.8 1994.41
  4890.1 1993.71  4895.4 1992.64  4926.7 1991.41  4978.5 1991.34  4984.0 1990.34
  4995.2 1989.56  4995.4 1989.06  4998.9 1989.06  4999.2 1989.56  5009.8 1990.12
  5015.1 1989.72  5020.9 1990.97  5031.5 1992.06  5063.3 1994.30  5071.7 1995.42
  5084.5 1995.72  5102.7 1997.87  5161.2 1999.65  5164.6 2000.23  5195.5 1999.79
  5211.7 2002.19  5221.2 2002.70  5232.9 2005.19  5243.5 2003.77  5249.4 2001.10
#Mann=4,-1,0
  4666.5    0.16       0  4995.2    0.07       0  4999.2    0.16       0
  5161.2   0.035       0
Bank Sta=4995.2,4999.2
Exp/Cntr=0.3,0.1

Type RM Length L Ch R = 1,7483,81,81,81
BEGIN DESCRIPTION:
Elm 01 25 7482.81
END DESCRIPTION:
XS GIS Cut Line= 3
      1531513.99      6804309.69      1531644.20      6804088.33
      1531726.66      6803914.74
#Sta/Elev= 30
  4735.0 1998.00  4744.8 1997.91  4750.6 1997.30  4766.3 1997.39  4772.1 1996.81
  4818.2 1996.12  4840.5 1996.64  4846.3 1996.00  4876.2 1996.00  4899.1 1995.01
  4911.0 1993.00  4942.0 1989.54  4979.2 1989.67  4994.8 1989.05  5001.5 1988.33
  5005.1 1987.16  5005.3 1986.66  5008.8 1986.66  5009.1 1987.16  5014.3 1989.45
  5029.8 1991.82  5047.0 1993.83  5052.5 1993.05  5058.6 1994.50  5080.8 1994.00
  5098.0 1994.98  5158.2 1995.11  5166.1 1995.71  5171.7 1995.07  5184.0 1995.66
#Mann=3,-1,0
  4735.0    0.16       0  5005.1    0.07       0  5009.1    0.16       0
Bank Sta=5005.1,5009.1
Exp/Cntr=0.3,0.1

Type RM Length L Ch R = 1,7402,228,228,228
BEGIN DESCRIPTION:
Elm 01 25 7401.89
END DESCRIPTION:
XS GIS Cut Line= 3
      1531544.38      6804340.06      1531704.96      6804138.24
      1531781.64      6804011.78
#Sta/Elev= 30
  4737.3 1998.05  4796.0 1995.82  4810.4 1996.23  4816.8 1995.71  4831.2 1996.13
  4845.6 1995.34  4880.9 1995.72  4909.7 1994.44  4924.1 1992.76  4938.5 1992.34
  4953.0 1990.84  4959.3 1991.41  4973.8 1990.80  4981.8 1989.38  4988.2 1988.88
  4992.2 1987.68  4998.3 1987.68  5003.1 1985.74  5007.0 1985.67  5007.2 1985.17
  5010.7 1985.17  5011.0 1985.67  5018.6 1986.65  5024.5 1985.79  5030.6 1986.08
  5040.0 1988.23  5082.6 1991.15  5089.1 1991.98  5125.3 1993.56  5143.1 1993.62
#Mann=3,-1,0
  4737.3    0.16       0  5007.0    0.07       0  5011.0    0.16       0
Bank Sta=5007,5011
Exp/Cntr=0.3,0.1

Type RM Length L Ch R = 1,7174,206,206,206
BEGIN DESCRIPTION:
Elm 01 25 7174.1
END DESCRIPTION:
XS GIS Cut Line= 4
      1531537.84      6804535.40      1531843.85      6804298.83
      1532025.45      6804157.74      1532054.61      6804001.19
#Sta/Elev= 30
  4561.4 2003.10  4579.2 2001.66  4608.2 2001.72  4699.6 1997.71  4722.1 1997.71
  4749.4 1995.94  4757.6 1994.08  4763.9 1994.40  4772.1 1992.36  4785.3 1991.37
  4813.7 1991.20  4842.7 1988.83  4892.5 1988.22  4907.0 1986.96  4936.0 1987.31
  4945.8 1985.79  4963.2 1987.03  4998.1 1984.52  4998.4 1984.02  5002.4 1984.52
  5013.0 1985.03  5021.1 1987.46  5056.4 1986.97  5077.2 1989.66  5099.8 1986.56
  5177.0 1988.18  5228.7 1988.25  5279.6 1991.67  5293.8 1991.04  5337.4 1992.35
#Mann=5,-1,0
  4561.4    0.07       0  4998.1    0.07       0  5002.4    0.07       0
  5177.0    0.16       0  5293.8    0.07       0
Bank Sta=4998.1,5002.4
Exp/Cntr=0.3,0.1

Type RM Length L Ch R = 1,6968,177,177,177
BEGIN DESCRIPTION:
Elm 01 25 6967.5
END DESCRIPTION:
XS GIS Cut Line= 3
      1531633.37      6804663.40      1531895.94      6804444.23
      1532261.08      6804143.91
#Sta/Elev= 30
  4653.0 1998.77  4721.4 1999.34  4743.5 1997.17  4828.1 1996.28  4891.9 1993.33
  4902.1 1991.29  4920.5 1985.66  4941.7 1982.26  4955.7 1983.61  4998.6 1982.62
  5048.1 1987.01  5084.4 1988.05  5097.6 1987.56  5105.5 1985.65  5112.0 1986.17
  5119.9 1984.49  5126.3 1984.92  5134.2 1981.85  5167.2 1979.95  5167.5 1979.45
  5171.5 1979.95  5183.7 1982.28  5190.2 1981.12  5198.1 1984.26  5204.5 1983.10
  5212.4 1985.81  5254.0 1989.44  5382.2 1991.81  5409.5 1991.31  5467.8 1991.67
#Mann=5,-1,0
  4653.0    0.07       0  4902.1    0.16       0  5167.2    0.07       0
  5171.5    0.16       0  5409.5    0.07       0
Bank Sta=5167.2,5171.5
Exp/Cntr=0.3,0.1

Type RM Length L Ch R = 1,6791,164,164,164
BEGIN DESCRIPTION:
Elm 01 25 6791.06
END DESCRIPTION:
XS GIS Cut Line= 3
      1531757.03      6804719.85      1532013.12      6804552.74
      1532308.23      6804183.85
#Sta/Elev= 30
  4690.3 1994.97  4885.4 1991.02  4914.7 1988.95  4927.5 1985.64  4950.6 1982.78
  4963.7 1979.27  4972.9 1978.33  4978.9 1978.15  4996.1 1981.13  5001.6 1981.13
  5007.8 1979.76  5022.2 1980.96  5028.6 1978.41  5040.9 1977.79  5041.1 1977.29
  5045.2 1977.79  5065.5 1978.04  5092.7 1982.76  5129.5 1983.19  5150.3 1985.55
  5199.9 1985.00  5243.1 1988.38  5249.6 1987.61  5257.6 1988.36  5264.0 1986.68
  5278.4 1987.97  5299.2 1987.42  5328.0 1989.50  5343.5 1989.48  5468.5 1991.31
#Mann=4,-1,0
  4690.3    0.07       0  5040.9    0.07       0  5045.2    0.07       0
  5343.5    0.07       0
Bank Sta=5040.9,5045.2
Exp/Cntr=0.3,0.1

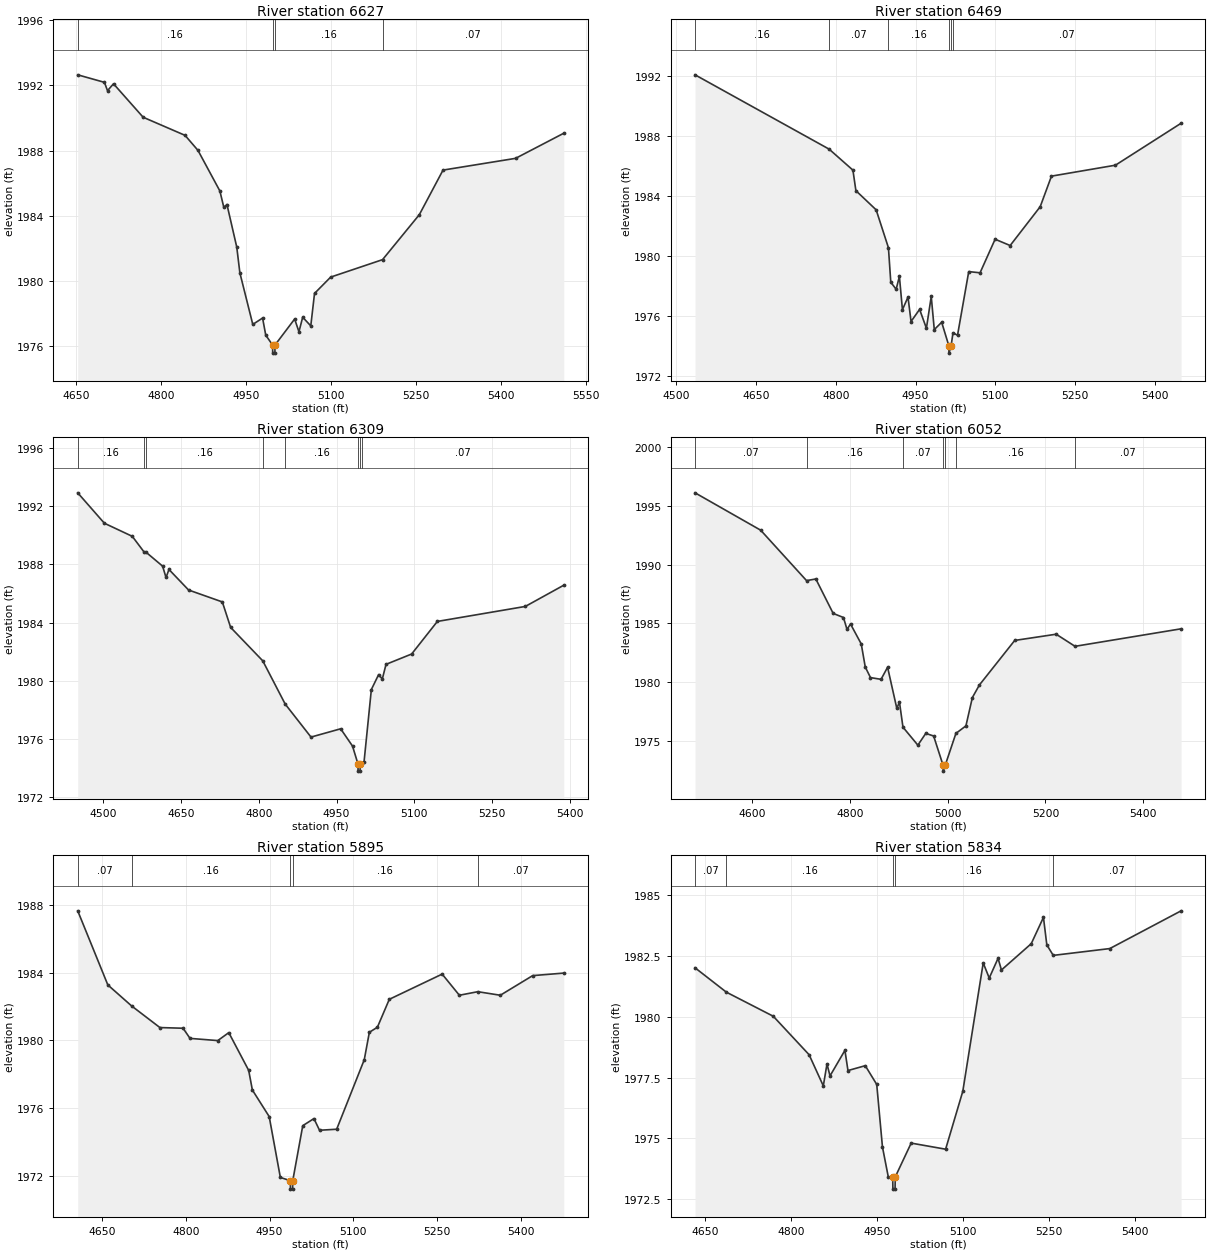
Type RM Length L Ch R = 1,6627,158,158,158
BEGIN DESCRIPTION:
Elm 01 25 6626.6
END DESCRIPTION:
XS GIS Cut Line= 3
      1531817.79      6804813.16      1532132.48      6804665.59
      1532516.63      6804329.18
#Sta/Elev= 30
  4652.9 1992.64  4700.0 1992.18  4705.5 1991.67  4716.1 1992.09  4768.4 1990.04
  4842.4 1988.93  4865.2 1988.01  4903.9 1985.52  4910.9 1984.51  4916.4 1984.69
  4933.7 1982.08  4939.2 1980.50  4962.0 1977.34  4979.3 1977.73  4984.9 1976.68
  4996.9 1976.08  4997.2 1975.58  5001.0 1975.58  5001.3 1976.08  5035.9 1977.67
  5043.5 1976.89  5050.1 1977.78  5064.4 1977.25  5071.0 1979.24  5099.5 1980.24
  5191.1 1981.31  5256.1 1984.07  5297.9 1986.80  5426.0 1987.52  5511.1 1989.06
#Mann=4,-1,0
  4652.9    0.16       0  4996.9    0.07       0  5001.3    0.16       0
  5191.1    0.07       0
Bank Sta=4996.9,5001.3
Exp/Cntr=0.3,0.1

Type RM Length L Ch R = 1,6469,160,160,160
BEGIN DESCRIPTION:
Elm 01 25 6469.23
END DESCRIPTION:
XS GIS Cut Line= 3
      1531852.56      6804906.46      1532260.52      6804685.12
      1532580.85      6804369.12
#Sta/Elev= 30
  4535.4 1992.09  4787.6 1987.13  4832.3 1985.73  4837.9 1984.36  4876.0 1983.08
  4899.1 1980.55  4903.5 1978.25  4913.6 1977.78  4919.7 1978.64  4925.4 1976.42
  4935.9 1977.26  4941.6 1975.63  4957.7 1976.44  4970.5 1975.18  4979.6 1977.30
  4985.3 1975.09  4999.2 1975.58  5012.6 1974.02  5012.9 1973.52  5017.0 1974.02
  5020.5 1974.88  5029.0 1974.71  5050.1 1978.96  5071.4 1978.88  5099.7 1981.12
  5128.0 1980.70  5184.5 1983.29  5205.7 1985.33  5326.0 1986.06  5449.5 1988.86
#Mann=6,-1,0
  4535.4    0.16       0  4787.6    0.07       0  4899.1    0.16       0
  5012.6    0.07       0  5017.0    0.16       0  5020.5    0.07       0
Bank Sta=5012.6,5017
Exp/Cntr=0.3,0.1

Type RM Length L Ch R = 1,6309,257,257,257
BEGIN DESCRIPTION:
Elm 01 25 6308.8
END DESCRIPTION:
XS GIS Cut Line= 3
      1531921.96      6805006.31      1532397.24      6804741.54
      1532680.74      6804468.86
#Sta/Elev= 30
  4450.8 1992.92  4502.2 1990.83  4556.0 1989.93  4578.4 1988.87  4582.8 1988.83
  4614.5 1987.88  4621.1 1987.10  4626.8 1987.65  4664.6 1986.24  4729.7 1985.42
  4745.7 1983.67  4807.7 1981.37  4850.9 1978.40  4900.7 1976.13  4957.9 1976.70
  4980.8 1975.51  4991.2 1974.29  4991.5 1973.79  4995.3 1973.79  4995.6 1974.29
  4998.2 1974.33  5002.9 1974.39  5017.1 1979.40  5031.2 1980.43  5038.2 1980.12
  5045.4 1981.13  5094.8 1981.84  5144.4 1984.08  5314.0 1985.11  5388.2 1986.57
#Mann=8,-1,0
  4450.8    0.16       0  4578.4    0.07       0  4582.8    0.16       0
  4807.7    0.07       0  4850.9    0.16       0  4991.2    0.07       0
  4995.6    0.16       0  4998.2    0.07       0
Bank Sta=4991.2,4995.6
Exp/Cntr=0.3,0.1

Type RM Length L Ch R = 1,6052,157,157,157
BEGIN DESCRIPTION:
Elm 01 25 6051.7
END DESCRIPTION:
XS GIS Cut Line= 4
      1531937.85      6805240.73      1532163.79      6805021.34
      1532353.84      6804945.53      1532647.80      6804571.59
#Sta/Elev= 30
  4482.6 1996.11  4617.0 1992.93  4710.9 1988.64  4729.9 1988.78  4765.4 1985.85
  4786.5 1985.50  4793.7 1984.49  4800.9 1984.95  4822.9 1983.25  4831.1 1981.29
  4841.8 1980.39  4863.4 1980.24  4876.8 1981.27  4895.7 1977.77  4901.1 1978.31
  4908.3 1976.17  4938.8 1974.64  4955.0 1975.64  4971.1 1975.42  4990.4 1972.93
  4990.7 1972.43  4994.8 1972.93  5016.7 1975.64  5037.2 1976.28  5050.4 1978.69
  5064.8 1979.76  5137.1 1983.55  5222.0 1984.08  5260.6 1983.05  5477.8 1984.54
#Mann=7,-1,0
  4482.6    0.07       0  4710.9    0.16       0  4908.3    0.07       0
  4990.4    0.07       0  4994.8    0.07       0  5016.7    0.16       0
  5260.6    0.07       0
Bank Sta=4990.4,4994.8
Exp/Cntr=0.3,0.1

Type RM Length L Ch R = 1,5895,61,61,61
BEGIN DESCRIPTION:
Elm 01 25 5919.27
END DESCRIPTION:
XS GIS Cut Line= 4
      1532378.37      6805420.04      1532458.19      6805124.65
      1532446.42      6804904.91      1532627.26      6804612.33
#Sta/Elev= 30
  4606.6 1987.65  4660.5 1983.27  4703.0 1982.03  4753.7 1980.75  4795.2 1980.71
  4807.6 1980.11  4857.3 1979.98  4877.0 1980.45  4912.6 1978.22  4919.2 1977.06
  4949.3 1975.49  4969.3 1971.89  4987.1 1971.70  4987.4 1971.20  4991.2 1971.20
  4991.5 1971.70  5009.4 1974.95  5029.4 1975.37  5039.4 1974.68  5070.1 1974.74
  5119.5 1978.85  5128.6 1980.47  5143.0 1980.77  5164.3 1982.42  5258.9 1983.91
  5289.7 1982.66  5322.7 1982.87  5363.0 1982.66  5420.9 1983.82  5476.6 1983.97
#Mann=5,-1,0
  4606.6    0.07       0  4703.0    0.16       0  4987.1    0.07       0
  4991.5    0.16       0  5322.7    0.07       0
Bank Sta=4987.1,4991.5
Exp/Cntr=0.3,0.1

Type RM Length L Ch R = 1,5834,240,240,240
BEGIN DESCRIPTION:
Elm 01 25 8.0
END DESCRIPTION:
XS GIS Cut Line= 4
      1532424.86      6805379.64      1532516.82      6805111.74
      1532505.05      6804892.00      1532686.34      6804598.70
#Sta/Elev= 30
  4633.1 1982.01  4687.7 1981.01  4769.6 1980.02  4832.1 1978.44  4856.9 1977.16
  4863.3 1978.06  4868.6 1977.57  4894.6 1978.62  4899.9 1977.79  4930.1 1977.99
  4950.1 1977.22  4960.1 1974.65  4970.2 1973.43  4978.0 1973.42  4978.3 1972.92
  4982.1 1972.92  4982.4 1973.42  5010.2 1974.81  5070.3 1974.56  5100.3 1976.94
  5135.9 1982.21  5146.4 1981.59  5161.8 1982.40  5167.7 1981.92  5219.7 1983.00
  5241.0 1984.08  5246.9 1982.95  5258.1 1982.52  5356.8 1982.80  5481.2 1984.35
#Mann=5,-1,0
  4633.1    0.07       0  4687.7    0.16       0  4978.0    0.07       0
  4982.4    0.16       0  5258.1    0.07       0
Bank Sta=4978,4982.4
Exp/Cntr=0.3,0.1

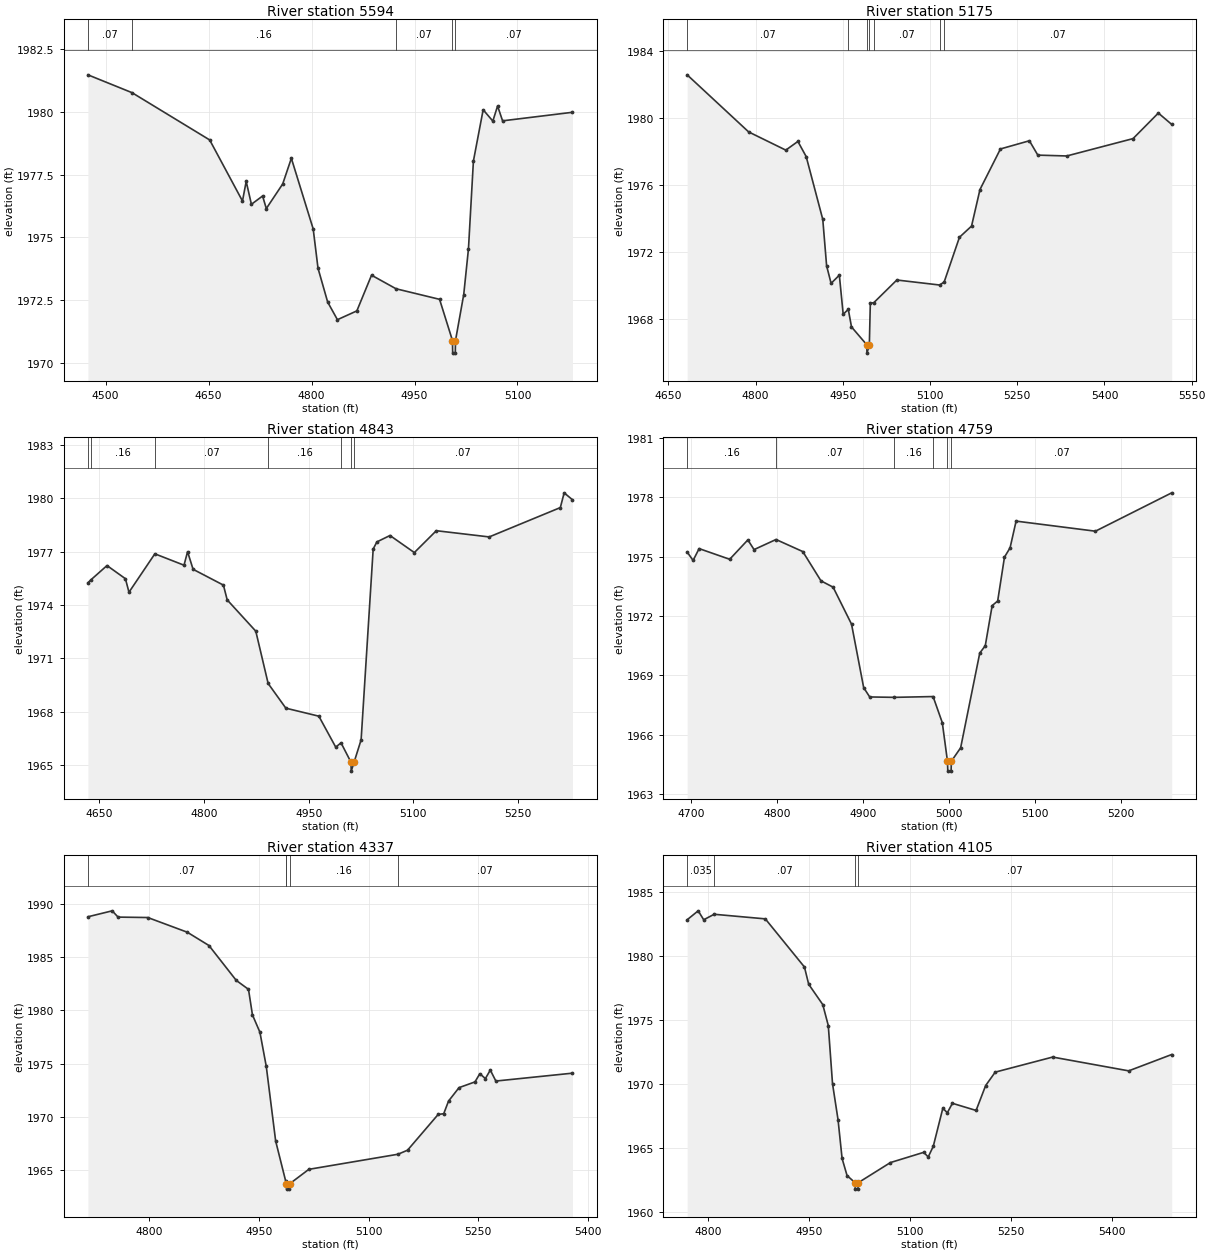
Type RM Length L Ch R = 1,5594,419,419,419
BEGIN DESCRIPTION:
Elm 01 25 5586.89
END DESCRIPTION:
XS GIS Cut Line= 3
      1532442.61      6805388.08      1532555.11      6805116.42
      1532839.25      6804818.26
#Sta/Elev= 30
  4474.2 1981.47  4538.5 1980.76  4651.6 1978.88  4699.4 1976.45  4704.8 1977.23
  4712.4 1976.32  4728.7 1976.65  4734.1 1976.15  4758.0 1977.13  4770.6 1978.15
  4802.4 1975.34  4809.4 1973.78  4823.5 1972.43  4837.7 1971.73  4866.0 1972.08
  4887.4 1973.50  4923.1 1972.96  4986.5 1972.54  5005.3 1970.90  5005.6 1970.40
  5009.4 1970.40  5009.7 1970.90  5021.7 1972.73  5028.6 1974.55  5035.8 1978.04
  5050.0 1980.08  5064.1 1979.63  5071.0 1980.23  5078.3 1979.64  5180.1 1979.98
#Mann=5,-1,0
  4474.2    0.07       0  4538.5    0.16       0  4923.1    0.07       0
  5005.3    0.07       0  5009.7    0.07       0
Bank Sta=5005.3,5009.7
Exp/Cntr=0.3,0.1

Type RM Length L Ch R = 1,5175,332,332,332
BEGIN DESCRIPTION:
Elm 01 25 5175.43
END DESCRIPTION:
XS GIS Cut Line= 3
      1532444.96      6805446.85      1532685.87      6805238.50
      1533001.75      6804831.75
#Sta/Elev= 30
  4682.2 1982.60  4788.0 1979.18  4851.9 1978.09  4872.7 1978.61  4887.0 1977.70
  4915.5 1973.94  4922.1 1971.16  4929.8 1970.11  4944.0 1970.60  4950.6 1968.26
  4959.4 1968.55  4964.9 1967.50  4991.2 1966.43  4991.5 1965.93  4995.6 1966.43
  4997.3 1968.94  5002.9 1968.94  5042.9 1970.31  5116.5 1970.01  5124.3 1970.19
  5150.6 1972.87  5171.4 1973.54  5185.9 1975.73  5221.1 1978.16  5270.9 1978.65
  5285.4 1977.79  5335.2 1977.74  5449.2 1978.78  5492.7 1980.31  5515.7 1979.63
#Mann=7,-1,0
  4682.2    0.07       0  4959.4    0.16       0  4991.2    0.07       0
  4995.6    0.16       0  5002.9    0.07       0  5116.5    0.16       0
  5124.3    0.07       0
Bank Sta=4991.2,4995.6
Exp/Cntr=0.3,0.1

Type RM Length L Ch R = 1,4843,84,84,84
BEGIN DESCRIPTION:
Elm 01 25 4856.82
END DESCRIPTION:
XS GIS Cut Line= 3
      1532658.34      6805355.70      1532834.14      6805313.52
      1533026.59      6804837.01
#Sta/Elev= 30
  4633.5 1975.24  4637.9 1975.41  4660.9 1976.21  4687.3 1975.47  4692.4 1974.71
  4729.5 1976.87  4771.3 1976.23  4776.4 1976.99  4784.3 1976.00  4827.8 1975.11
  4833.2 1974.28  4874.2 1972.52  4891.9 1969.58  4917.3 1968.19  4964.6 1967.74
  4988.8 1966.00  4996.4 1966.24  5010.7 1965.15  5011.0 1964.65  5015.1 1965.15
  5025.2 1966.41  5042.5 1977.14  5047.8 1977.54  5066.6 1977.90  5101.5 1976.94
  5133.0 1978.17  5208.8 1977.82  5310.8 1979.47  5316.3 1980.30  5328.2 1979.91
#Mann=7,-1,0
  4633.5    0.07       0  4637.9    0.16       0  4729.5    0.07       0
  4891.9    0.16       0  4996.4    0.07       0  5010.7    0.07       0
  5015.1    0.07       0
Bank Sta=5010.7,5015.1
Exp/Cntr=0.3,0.1

Type RM Length L Ch R = 1,4759,422,422,422
BEGIN DESCRIPTION:
Elm 01 25 4758.84
END DESCRIPTION:
XS GIS Cut Line= 3
      1532747.22      6805409.93      1532961.47      6805203.78
      1533128.57      6804997.62
#Sta/Elev= 30
  4695.8 1975.24  4702.7 1974.81  4709.7 1975.41  4745.2 1974.87  4766.3 1975.85
  4773.5 1975.36  4799.0 1975.87  4830.1 1975.26  4851.2 1973.78  4865.3 1973.46
  4886.7 1971.59  4900.8 1968.38  4907.8 1967.91  4936.4 1967.89  4981.4 1967.93
  4992.1 1966.61  4998.1 1964.66  4998.5 1964.16  5002.3 1964.16  5002.6 1964.66
  5013.4 1965.34  5035.6 1970.13  5042.0 1970.50  5050.0 1972.53  5056.4 1972.76
  5064.3 1974.98  5070.8 1975.45  5077.8 1976.80  5169.9 1976.29  5258.5 1978.23
#Mann=6,-1,0
  4695.8    0.16       0  4799.0    0.07       0  4936.4    0.16       0
  4981.4    0.07       0  4998.1    0.07       0  5002.6    0.07       0
Bank Sta=4998.1,5002.6
Exp/Cntr=0.3,0.1

Type RM Length L Ch R = 1,4337,232,232,232
BEGIN DESCRIPTION:
Elm 01 25 4336.82
END DESCRIPTION:
XS GIS Cut Line= 3
      1532646.77      6805644.33      1532902.88      6805542.32
      1533193.66      6805288.43
#Sta/Elev= 30
  4716.8 1988.80  4750.0 1989.36  4758.0 1988.77  4798.6 1988.73  4852.5 1987.35
  4882.1 1986.10  4919.4 1982.82  4936.1 1981.98  4941.5 1979.58  4951.7 1977.95
  4960.4 1974.73  4973.2 1967.72  4986.9 1963.95  4987.8 1963.70  4988.1 1963.20
  4992.0 1963.20  4992.3 1963.70  5018.5 1965.06  5140.3 1966.48  5153.3 1966.86
  5195.1 1970.22  5202.7 1970.29  5209.3 1971.48  5223.6 1972.74  5245.4 1973.28
  5252.0 1974.05  5259.6 1973.59  5266.3 1974.39  5273.9 1973.36  5378.5 1974.10
#Mann=5,-1,0
  4716.8    0.07       0  4986.9    0.16       0  4987.8    0.07       0
  4992.3    0.16       0  5140.3    0.07       0
Bank Sta=4987.8,4992.3
Exp/Cntr=0.3,0.1

Type RM Length L Ch R = 1,4105,262,262,262
BEGIN DESCRIPTION:
Elm 01 25 4105.2
END DESCRIPTION:
XS GIS Cut Line= 3
      1532905.03      6805811.44      1533089.51      6805670.36
      1533412.89      6805305.75
#Sta/Elev= 30
  4769.4 1982.86  4785.8 1983.56  4794.0 1982.86  4809.5 1983.29  4885.5 1982.93
  4943.6 1979.16  4949.9 1977.81  4970.8 1976.22  4979.0 1974.58  4985.3 1970.02
  4993.5 1967.20  4999.5 1964.17  5006.9 1962.83  5018.9 1962.27  5019.2 1961.77
  5023.1 1961.77  5023.4 1962.27  5071.3 1963.85  5120.7 1964.65  5127.4 1964.29
  5134.9 1965.12  5149.1 1968.10  5155.8 1967.75  5163.3 1968.49  5198.5 1967.93
  5212.7 1969.88  5226.9 1970.93  5312.2 1972.11  5425.1 1971.03  5489.0 1972.31
#Mann=4,-1,0
  4769.4   0.035       0  4809.5    0.07       0  5018.9    0.07       0
  5023.4    0.07       0
Bank Sta=5018.9,5023.4
Exp/Cntr=0.3,0.1

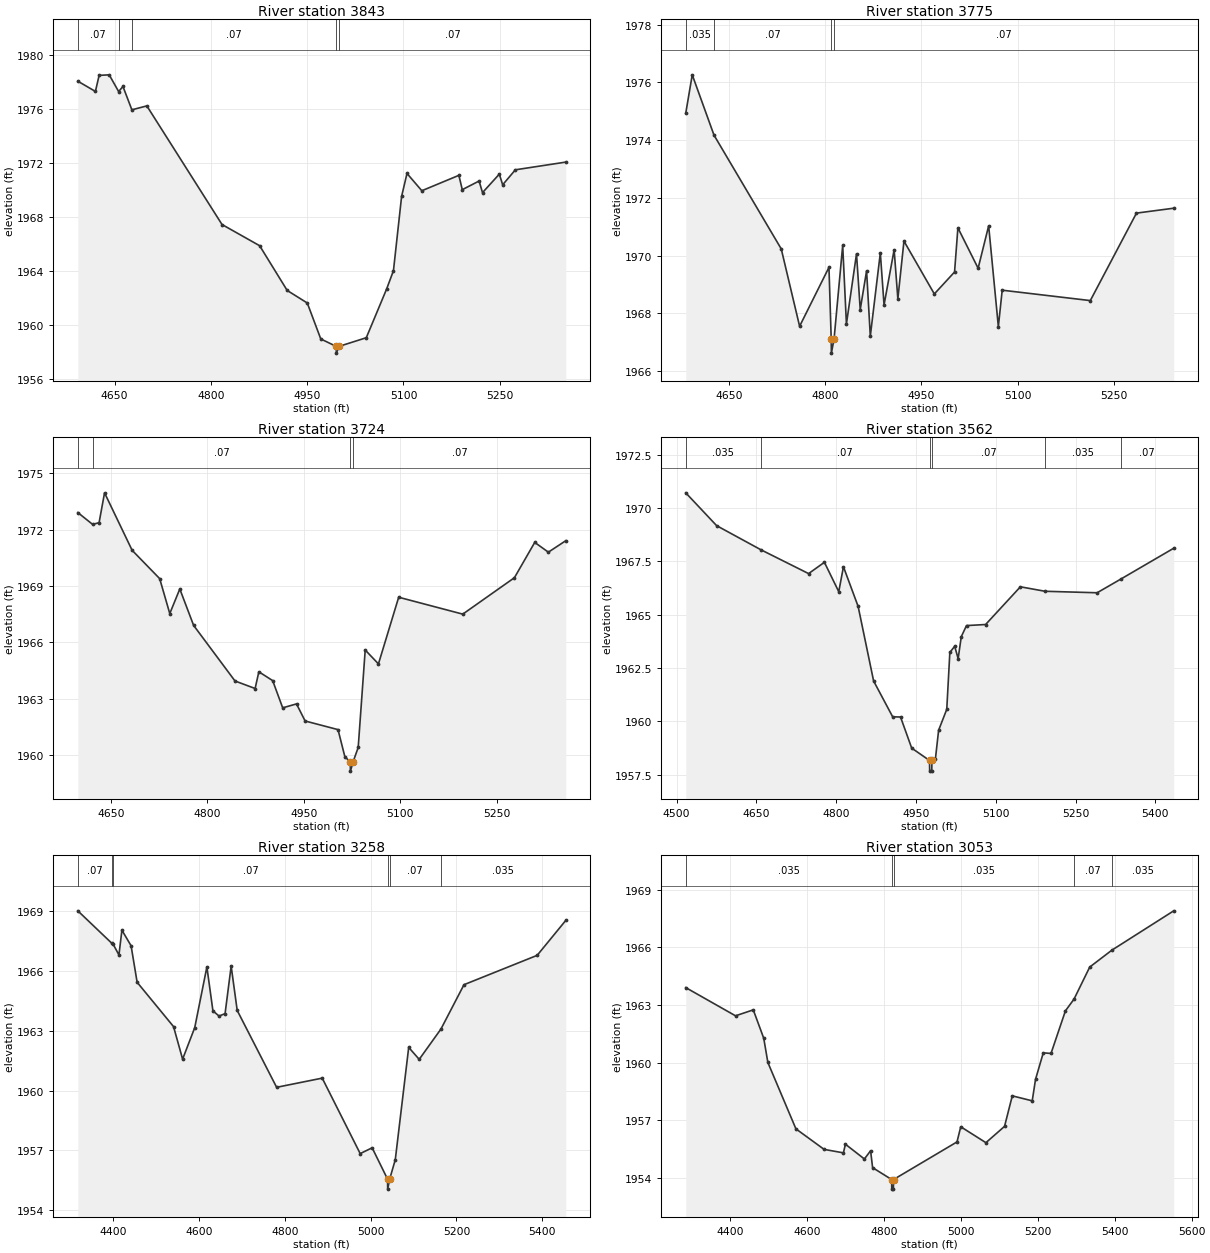
Type RM Length L Ch R = 1,3843,68,68,68
BEGIN DESCRIPTION:
Elm 01 25 6.0
END DESCRIPTION:
XS GIS Cut Line= 3
      1533007.30      6805867.45      1533313.31      6805687.32
      1533442.64      6805303.62
#Sta/Elev= 30
  4592.8 1978.04  4620.2 1977.28  4626.0 1978.47  4641.7 1978.51  4656.4 1977.27
  4663.1 1977.65  4677.0 1975.92  4700.3 1976.21  4817.4 1967.43  4876.0 1965.86
  4918.9 1962.55  4950.2 1961.62  4971.2 1958.96  4995.2 1958.41  4995.5 1957.91
  4999.7 1958.41  5042.1 1959.05  5073.8 1962.66  5084.4 1964.01  5097.1 1969.51
  5105.5 1971.21  5128.6 1969.93  5186.3 1971.07  5191.6 1970.01  5217.8 1970.65
  5223.1 1969.79  5249.3 1971.16  5254.5 1970.37  5274.3 1971.48  5352.8 1972.05
#Mann=5,-1,0
  4592.8    0.07       0  4656.4   0.035       0  4677.0    0.07       0
  4995.2    0.07       0  4999.7    0.07       0
Bank Sta=4995.2,4999.7
Exp/Cntr=0.3,0.1

Type RM Length L Ch R = 1,3775,51,51,51
BEGIN DESCRIPTION:
Elm 01 25 3777.48
END DESCRIPTION:
XS GIS Cut Line= 3
      1533072.18      6805878.68      1533378.14      6805698.57
      1533507.46      6805314.91
#Sta/Elev= 30
  4583.0 1974.93  4593.1 1976.26  4627.0 1974.17  4731.7 1970.23  4760.3 1967.55
  4806.0 1969.59  4809.5 1967.12  4809.8 1966.62  4814.0 1967.12  4827.4 1970.35
  4833.2 1967.63  4848.9 1970.06  4854.7 1968.13  4864.6 1969.47  4870.4 1967.21
  4886.0 1970.09  4891.8 1968.29  4907.5 1970.20  4913.3 1968.50  4922.8 1970.50
  4970.1 1968.67  5001.6 1969.43  5006.8 1970.96  5038.3 1969.56  5054.7 1971.03
  5069.8 1967.54  5075.8 1968.80  5213.0 1968.44  5284.9 1971.47  5342.9 1971.64
#Mann=4,-1,0
  4583.0   0.035       0  4627.0    0.07       0  4809.5    0.07       0
  4814.0    0.07       0
Bank Sta=4809.5,4814
Exp/Cntr=0.3,0.1

Type RM Length L Ch R = 1,3724,162,162,162
BEGIN DESCRIPTION:
Elm 01 25 5.0
END DESCRIPTION:
XS GIS Cut Line= 3
      1533116.44      6805895.43      1533422.47      6805715.29
      1533551.58      6805332.28
#Sta/Elev= 30
  4598.5 1972.92  4621.5 1972.29  4631.6 1972.38  4640.1 1973.97  4683.0 1970.91
  4725.9 1969.40  4741.6 1967.54  4757.2 1968.85  4778.7 1966.91  4843.1 1963.95
  4874.4 1963.55  4880.2 1964.44  4901.7 1963.97  4917.3 1962.52  4938.8 1962.73
  4952.2 1961.82  5003.4 1961.36  5014.1 1959.91  5022.4 1959.65  5022.7 1959.15
  5026.9 1959.65  5034.8 1960.41  5045.7 1965.60  5066.3 1964.86  5097.8 1968.41
  5197.5 1967.51  5277.9 1969.45  5309.5 1971.33  5330.7 1970.81  5357.8 1971.42
#Mann=4,-1,0
  4598.5   0.035       0  4621.5    0.07       0  5022.4    0.07       0
  5026.9    0.07       0
Bank Sta=5022.4,5026.9
Exp/Cntr=0.3,0.1

Type RM Length L Ch R = 1,3562,304,304,304
BEGIN DESCRIPTION:
Elm 01 25 3562.13
END DESCRIPTION:
XS GIS Cut Line= 3
      1533209.32      6806214.07      1533484.48      6805817.93
      1533706.19      6805443.82
#Sta/Elev= 30
  4517.3 1970.72  4575.3 1969.18  4658.4 1968.05  4748.2 1966.93  4777.9 1967.46
  4804.9 1966.08  4813.7 1967.25  4841.3 1965.39  4870.4 1961.89  4906.2 1960.21
  4921.0 1960.20  4942.0 1958.74  4975.5 1958.16  4975.8 1957.66  4979.7 1957.66
  4980.0 1958.16  4986.5 1958.22  4992.6 1959.58  5007.9 1960.56  5013.7 1963.23
  5022.8 1963.52  5029.3 1962.94  5035.2 1963.97  5045.0 1964.49  5080.9 1964.54
  5146.3 1966.31  5192.7 1966.10  5290.5 1966.03  5334.9 1966.67  5434.5 1968.12
#Mann=6,-1,0
  4517.3   0.035       0  4658.4    0.07       0  4975.5    0.07       0
  4980.0    0.07       0  5192.7   0.035       0  5334.9    0.07       0
Bank Sta=4975.5,4980
Exp/Cntr=0.3,0.1

Type RM Length L Ch R = 1,3258,205,205,205
BEGIN DESCRIPTION:
Elm 01 25 3362.01
END DESCRIPTION:
XS GIS Cut Line= 3
      1533263.16      6806391.68      1533687.99      6805949.63
      1533838.56      6805447.20
#Sta/Elev= 30
  4317.2 1969.00  4396.7 1967.37  4399.7 1967.32  4413.1 1966.79  4420.0 1968.03
  4441.4 1967.25  4455.5 1965.42  4540.4 1963.20  4561.5 1961.57  4589.8 1963.15
  4618.1 1966.19  4632.2 1963.99  4646.4 1963.73  4660.5 1963.85  4674.7 1966.23
  4688.8 1964.01  4780.7 1960.16  4887.0 1960.62  4975.5 1956.84  5003.4 1957.13
  5039.3 1955.56  5039.6 1955.06  5044.2 1955.56  5057.3 1956.53  5088.6 1962.16
  5113.1 1961.56  5163.8 1963.08  5217.5 1965.30  5388.1 1966.77  5454.8 1968.52
#Mann=6,-1,0
  4317.2    0.07       0  4396.7   0.035       0  4399.7    0.07       0
  5039.3    0.07       0  5044.2    0.07       0  5163.8   0.035       0
Bank Sta=5039.3,5044.2
Exp/Cntr=0.3,0.1

Type RM Length L Ch R = 1,3053,301,301,301
BEGIN DESCRIPTION:
Elm 01 25 3062.43
END DESCRIPTION:
XS GIS Cut Line= 3
      1533608.79      6806731.61      1533837.00      6805989.19
      1533890.29      6805501.10
#Sta/Elev= 30
  4285.7 1963.91  4415.0 1962.44  4461.1 1962.75  4488.3 1961.27  4499.0 1960.01
  4571.9 1956.55  4645.2 1955.48  4695.3 1955.30  4700.5 1955.75  4749.8 1954.98
  4765.9 1955.41  4771.1 1954.53  4820.6 1953.91  4820.9 1953.41  4825.1 1953.41
  4825.5 1953.91  4990.4 1955.87  5000.1 1956.66  5065.5 1955.83  5113.9 1956.68
  5134.0 1958.27  5185.8 1958.01  5194.4 1959.13  5214.5 1960.51  5234.6 1960.48
  5272.1 1962.70  5294.4 1963.31  5335.2 1964.98  5392.7 1965.86  5553.4 1967.91
#Mann=5,-1,0
  4285.7   0.035       0  4820.6   0.035       0  4825.5   0.035       0
  5294.4    0.07       0  5392.7   0.035       0
Bank Sta=4820.6,4825.5
Exp/Cntr=0.3,0.1

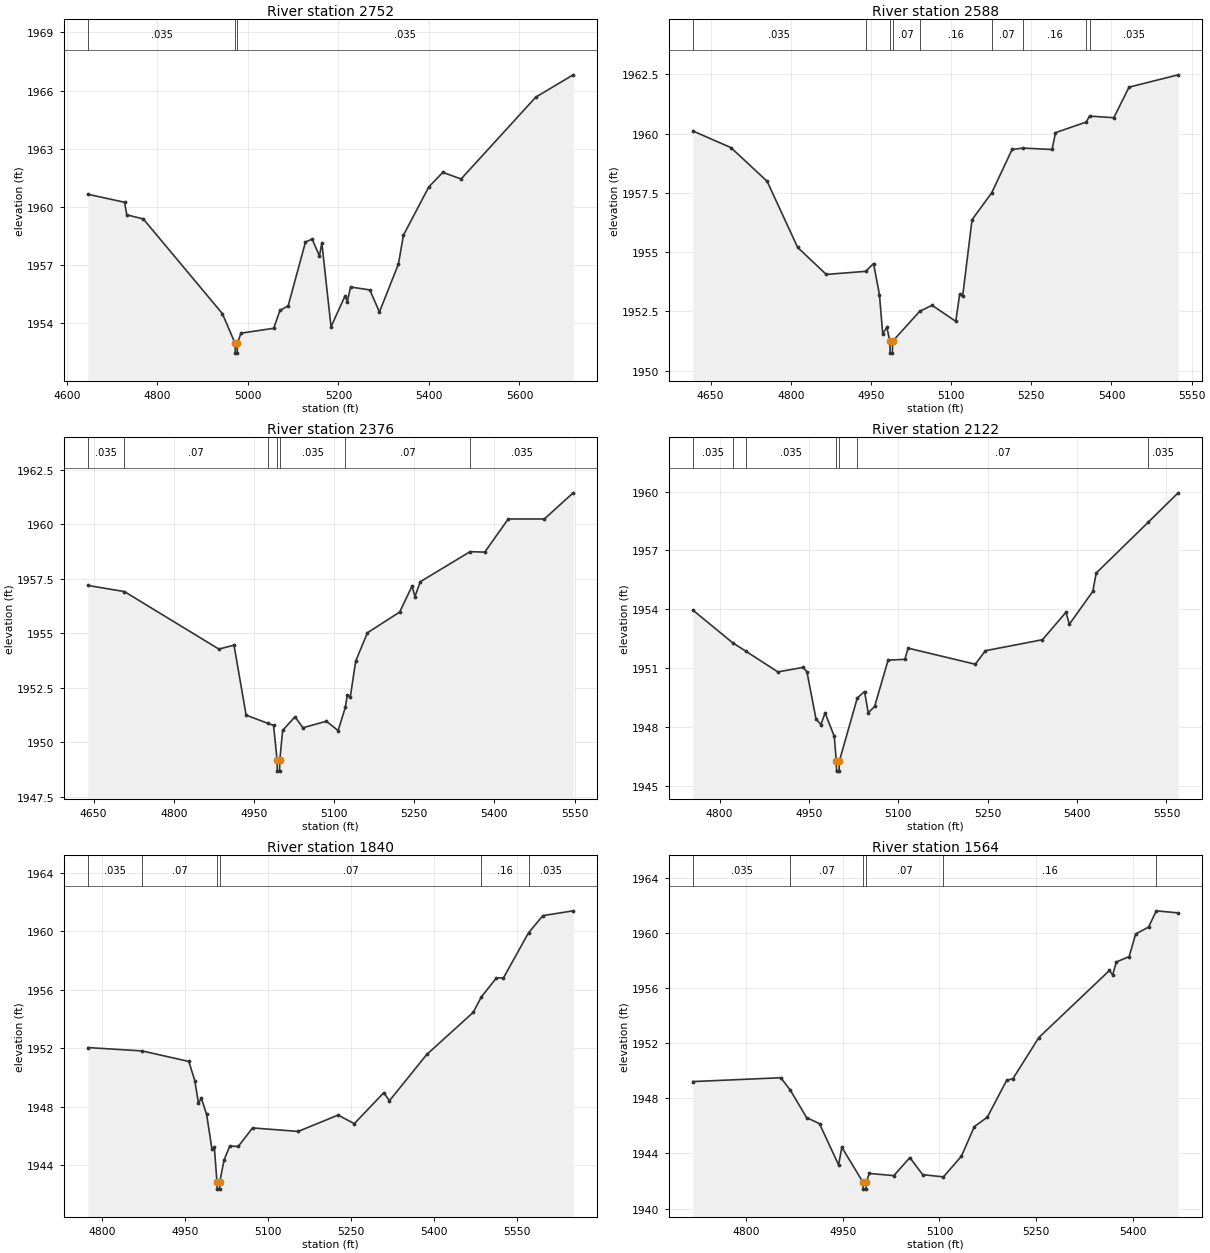
Type RM Length L Ch R = 1,2752,164,164,164
BEGIN DESCRIPTION:
Elm 01 25 2659.24
END DESCRIPTION:
XS GIS Cut Line= 3
      1533750.38      6806657.01      1533840.80      6806273.10
      1534067.45      6805634.65
#Sta/Elev= 30
  4646.7 1960.65  4727.5 1960.24  4732.6 1959.59  4769.0 1959.38  4943.6 1954.50
  4971.9 1952.96  4972.3 1952.46  4976.5 1952.46  4976.9 1952.96  4984.7 1953.49
  5057.1 1953.74  5070.8 1954.66  5089.0 1954.90  5127.3 1958.19  5142.0 1958.34
  5158.1 1957.47  5163.4 1958.14  5183.7 1953.82  5214.5 1955.40  5219.8 1955.12
  5226.9 1955.87  5269.4 1955.72  5290.6 1954.58  5332.7 1957.06  5343.6 1958.54
  5399.7 1961.03  5430.6 1961.78  5471.0 1961.44  5636.0 1965.66  5718.6 1966.81
#Mann=3,-1,0
  4646.7   0.035       0  4971.9   0.035       0  4976.9   0.035       0
Bank Sta=4971.9,4976.9
Exp/Cntr=0.3,0.1

Type RM Length L Ch R = 1,2588,212,212,212
BEGIN DESCRIPTION:
Elm 01 25 1.0
END DESCRIPTION:
XS GIS Cut Line= 3
      1533807.78      6806733.58      1533961.88      6806408.01
      1534187.58      6805908.86
#Sta/Elev= 30
  4616.7 1960.11  4687.9 1959.41  4755.6 1957.99  4812.7 1955.20  4866.3 1954.06
  4939.9 1954.19  4954.8 1954.52  4965.8 1953.21  4971.9 1951.56  4979.6 1951.83
  4985.4 1951.24  4985.8 1950.74  4990.0 1950.74  4990.4 1951.24  5041.0 1952.50
  5064.3 1952.76  5108.6 1952.08  5116.0 1953.23  5121.5 1953.14  5139.1 1956.37
  5175.8 1957.50  5214.0 1959.33  5234.1 1959.39  5288.8 1959.33  5295.2 1960.04
  5352.8 1960.49  5358.9 1960.74  5404.3 1960.67  5432.9 1961.96  5524.7 1962.48
#Mann=9,-1,0
  4616.7   0.035       0  4939.9    0.07       0  4985.4    0.07       0
  4990.4    0.07       0  5041.0    0.16       0  5175.8    0.07       0
  5234.1    0.16       0  5352.8    0.07       0  5358.9   0.035       0
Bank Sta=4985.4,4990.4
Exp/Cntr=0.3,0.1

Type RM Length L Ch R = 1,2376,254,254,254
BEGIN DESCRIPTION:
Elm 01 25 2376.11
END DESCRIPTION:
XS GIS Cut Line= 3
      1534014.01      6806761.91      1534168.07      6806436.42
      1534393.77      6805937.28
#Sta/Elev= 30
  4639.5 1957.19  4707.7 1956.91  4884.5 1954.27  4912.8 1954.45  4935.5 1951.24
  4976.4 1950.86  4986.8 1950.77  4993.5 1949.17  4993.8 1948.67  4998.1 1948.67
  4998.5 1949.17  5003.8 1950.54  5026.9 1951.16  5041.8 1950.66  5085.7 1950.96
  5107.6 1950.53  5121.0 1951.59  5124.9 1952.17  5130.4 1952.07  5140.5 1953.72
  5162.5 1955.02  5222.8 1955.97  5245.9 1957.16  5251.4 1956.68  5261.3 1957.36
  5354.5 1958.74  5382.0 1958.72  5425.9 1960.24  5493.5 1960.24  5547.4 1961.44
#Mann=7,-1,0
  4639.5   0.035       0  4707.7    0.07       0  4976.4   0.035       0
  4993.5   0.035       0  4998.5   0.035       0  5121.0    0.07       0
  5354.5   0.035       0
Bank Sta=4993.5,4998.5
Exp/Cntr=0.3,0.1

Type RM Length L Ch R = 1,2122,282,282,282
BEGIN DESCRIPTION:
Elm 01 25 2122.09
END DESCRIPTION:
XS GIS Cut Line= 3
      1534233.16      6806801.03      1534361.21      6806592.67
      1534610.79      6806080.50
#Sta/Elev= 30
  4755.3 1953.96  4821.8 1952.30  4843.9 1951.87  4897.9 1950.81  4940.5 1951.04
  4946.7 1950.81  4961.8 1948.43  4970.1 1948.12  4977.2 1948.72  4992.6 1947.52
  4996.0 1946.25  4996.4 1945.75  5000.7 1945.75  5001.0 1946.25  5031.2 1949.48
  5043.4 1949.81  5049.6 1948.72  5060.3 1949.05  5082.9 1951.41  5111.0 1951.45
  5116.5 1952.02  5229.2 1951.20  5246.2 1951.89  5341.9 1952.45  5381.4 1953.85
  5387.0 1953.24  5426.5 1954.92  5432.1 1955.85  5519.1 1958.43  5569.6 1959.94
#Mann=7,-1,0
  4755.3   0.035       0  4821.8    0.07       0  4843.9   0.035       0
  4996.0   0.035       0  5001.0   0.035       0  5031.2    0.07       0
  5519.1   0.035       0
Bank Sta=4996,5001
Exp/Cntr=0.3,0.1

Type RM Length L Ch R = 1,1840,276,276,276
BEGIN DESCRIPTION:
Elm 01 25 1840
END DESCRIPTION:
XS GIS Cut Line= 3
      1534517.46      6806937.72      1534599.93      6806725.05
      1534751.83      6806095.72
#Sta/Elev= 30
  4775.1 1952.04  4872.9 1951.81  4957.1 1951.09  4967.9 1949.78  4974.5 1948.24
  4979.8 1948.56  4989.3 1947.46  4998.9 1945.08  5003.2 1945.21  5007.9 1942.85
  5008.3 1942.35  5012.6 1942.35  5013.0 1942.85  5020.7 1944.34  5031.0 1945.30
  5046.3 1945.27  5072.2 1946.54  5154.5 1946.30  5226.5 1947.42  5255.7 1946.83
  5308.8 1948.95  5319.1 1948.40  5386.5 1951.57  5470.3 1954.45  5485.0 1955.51
  5512.2 1956.81  5524.8 1956.81  5570.0 1959.89  5595.9 1961.07  5650.6 1961.40
#Mann=6,-1,0
  4775.1   0.035       0  4872.9    0.07       0  5007.9    0.07       0
  5013.0    0.07       0  5485.0    0.16       0  5570.0   0.035       0
Bank Sta=5007.9,5013
Exp/Cntr=0.3,0.1

Type RM Length L Ch R = 1,1564,304,304,304
BEGIN DESCRIPTION:
Elm 01 25 1564.02
END DESCRIPTION:
XS GIS Cut Line= 3
      1534819.11      6806894.34      1534832.13      6806618.71
      1534803.98      6806142.18
#Sta/Elev= 30
  4717.2 1949.22  4853.7 1949.50  4868.4 1948.60  4893.7 1946.61  4913.8 1946.16
  4943.4 1943.17  4948.4 1944.45  4981.3 1941.91  4981.7 1941.41  4986.0 1941.41
  4986.4 1941.91  4991.0 1942.55  5029.1 1942.39  5054.0 1943.70  5074.0 1942.46
  5106.2 1942.30  5134.1 1943.80  5154.1 1945.95  5174.2 1946.63  5204.2 1949.30
  5214.2 1949.44  5254.3 1952.42  5363.9 1957.29  5368.9 1956.96  5374.5 1957.90
  5394.5 1958.30  5404.6 1959.94  5424.6 1960.44  5436.6 1961.62  5470.5 1961.47
#Mann=6,-1,0
  4717.2   0.035       0  4868.4    0.07       0  4981.3    0.07       0
  4986.4    0.07       0  5106.2    0.16       0  5436.6   0.035       0
Bank Sta=4981.3,4986.4
Exp/Cntr=0.3,0.1