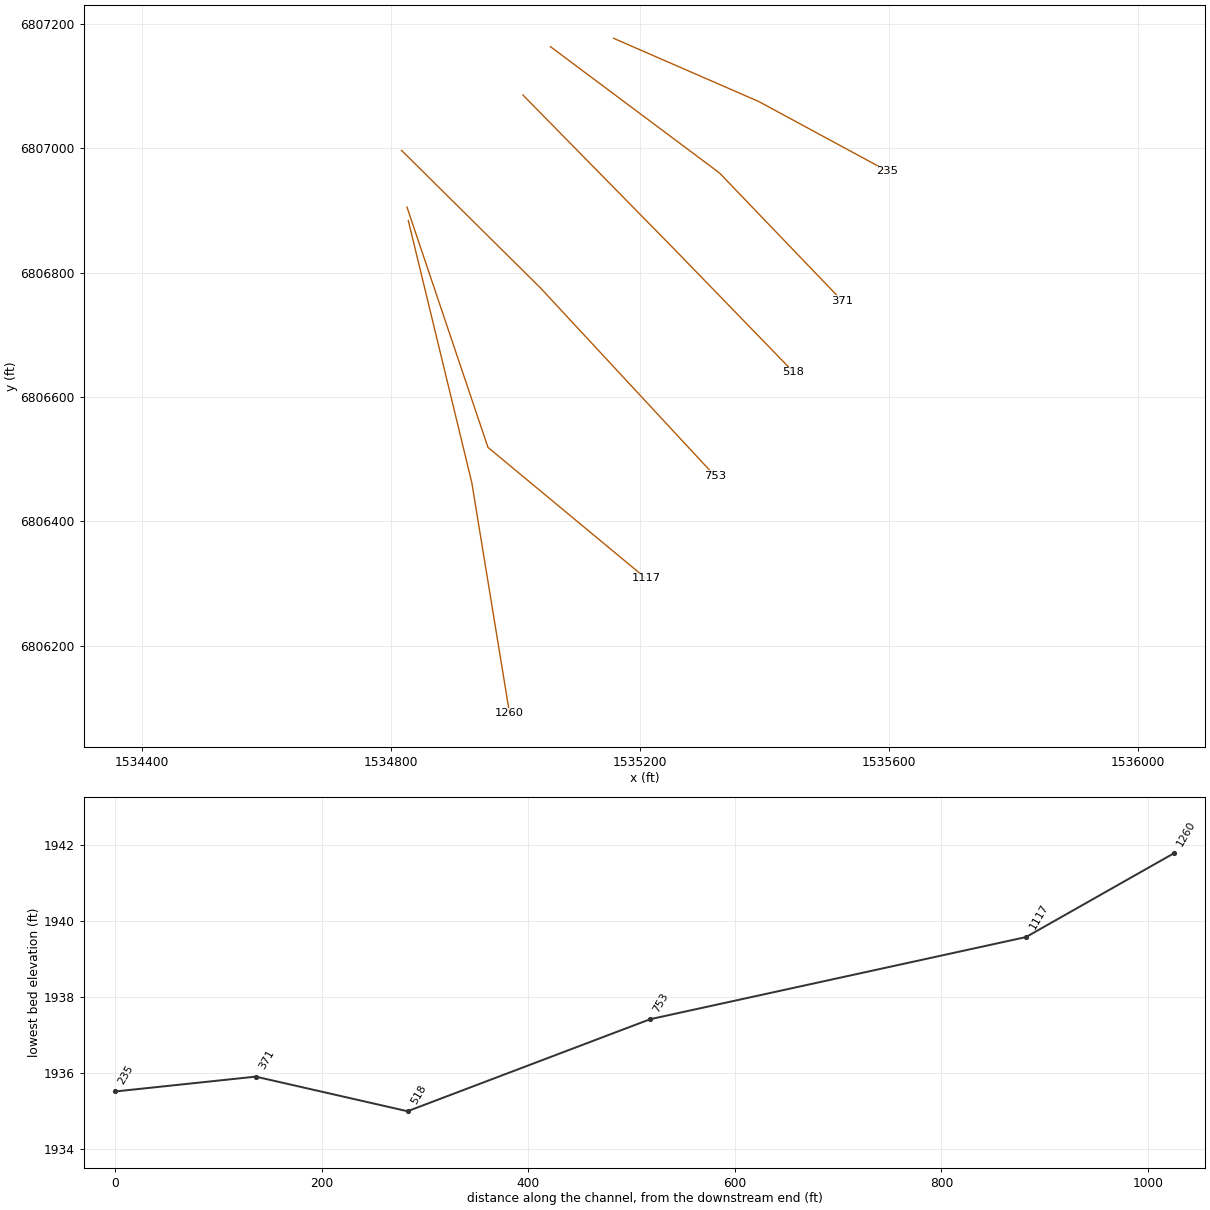
HEC-RAS study Elm 01 25.prj: Elm 01 25 Base Level Engineering

--- Elm 01 25.g01 (geometry) --- (continued)

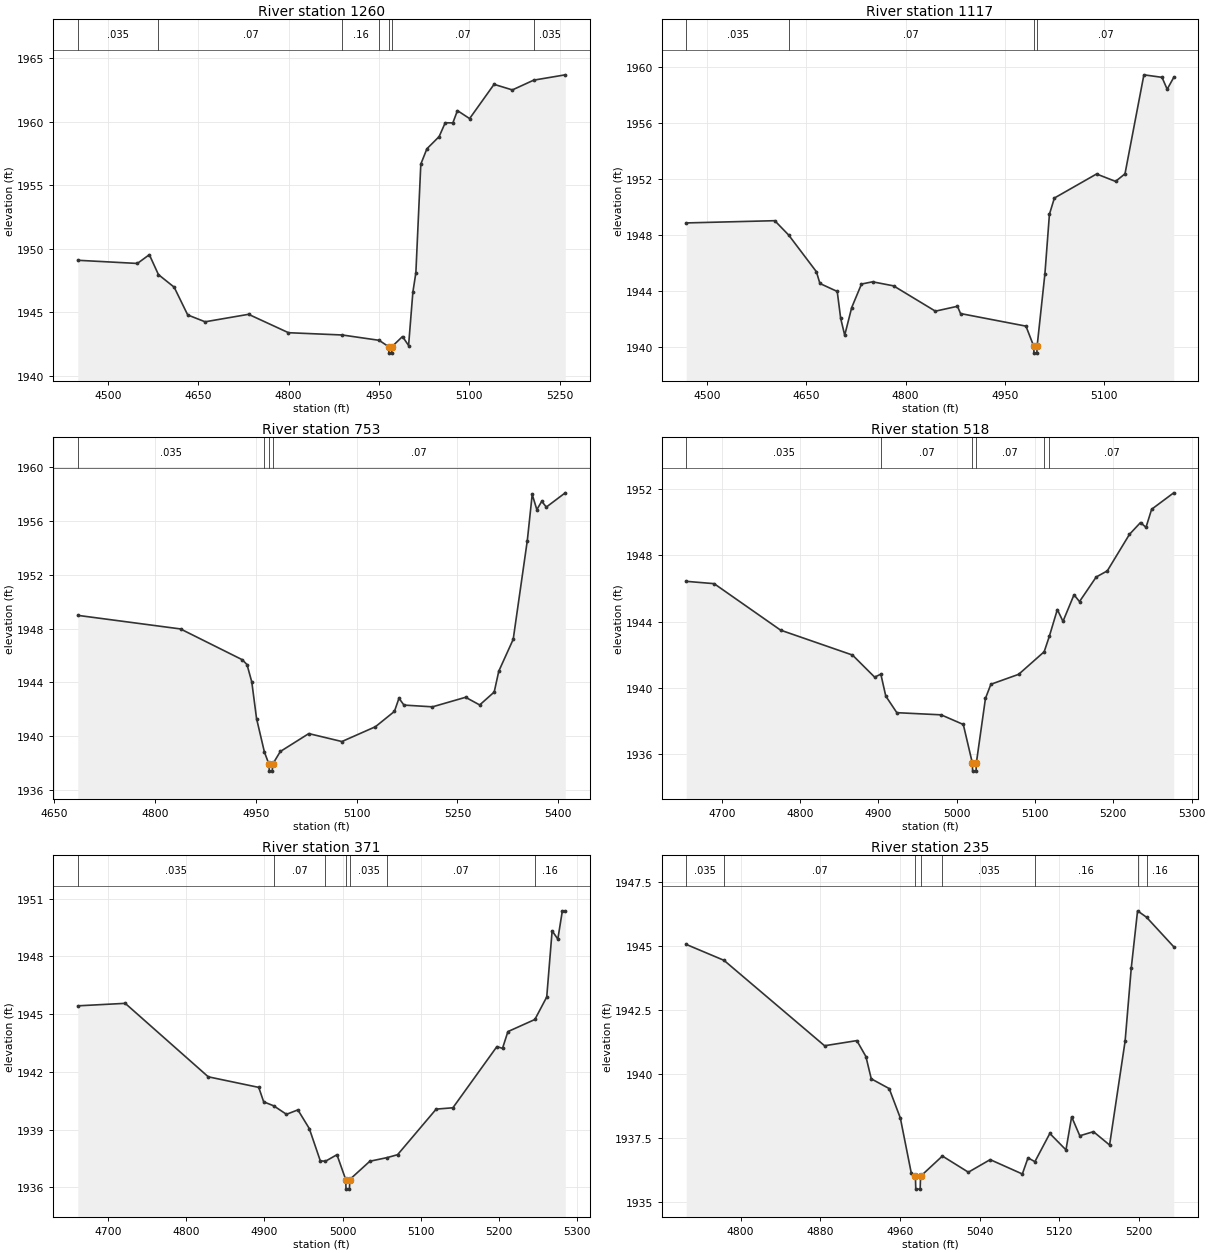
Type RM Length L Ch R = 1,1260,143,143,143
BEGIN DESCRIPTION:
Elm 01 25 1260.26
END DESCRIPTION:
XS GIS Cut Line= 3
      1534827.79      6806883.50      1534929.79      6806462.46
      1534990.56      6806091.32
#Sta/Elev= 30
  4450.1 1949.09  4549.0 1948.84  4568.9 1949.53  4584.0 1947.96  4610.1 1946.97
  4632.6 1944.78  4661.5 1944.24  4733.6 1944.83  4799.9 1943.38  4889.2 1943.20
  4950.4 1942.78  4966.4 1942.27  4966.7 1941.77  4971.1 1941.77  4971.5 1942.27
  4989.2 1943.08  4999.3 1942.37  5006.4 1946.57  5011.4 1948.11  5019.6 1956.67
  5029.7 1957.88  5050.0 1958.84  5060.1 1959.93  5072.8 1959.92  5080.4 1960.89
  5100.6 1960.26  5141.2 1962.96  5171.6 1962.52  5207.0 1963.29  5259.4 1963.71
#Mann=7,-1,0
  4450.1   0.035       0  4584.0    0.07       0  4889.2    0.16       0
  4950.4    0.07       0  4966.4    0.07       0  4971.5    0.07       0
  5207.0   0.035       0
Bank Sta=4966.4,4971.5
Exp/Cntr=0.3,0.1

Type RM Length L Ch R = 1,1117,364,364,364
BEGIN DESCRIPTION:
Elm 01 25 1117.01
END DESCRIPTION:
XS GIS Cut Line= 3
      1534825.63      6806905.16      1534955.83      6806518.89
      1535209.70      6806308.41
#Sta/Elev= 30
  4468.1 1948.88  4602.0 1949.04  4623.1 1948.01  4665.0 1945.39  4670.3 1944.55
  4696.5 1943.98  4701.7 1942.06  4707.8 1940.85  4718.4 1942.83  4733.2 1944.51
  4750.0 1944.67  4781.7 1944.38  4845.0 1942.57  4878.4 1942.92  4883.0 1942.40
  4982.0 1941.50  4993.7 1940.07  4994.1 1939.57  4998.5 1939.57  4998.9 1940.07
  5010.7 1945.26  5017.5 1949.50  5025.0 1950.66  5088.8 1952.38  5117.5 1951.85
  5131.8 1952.39  5160.4 1959.47  5187.8 1959.29  5195.6 1958.44  5205.5 1959.28
#Mann=4,-1,0
  4468.1   0.035       0  4623.1    0.07       0  4993.7    0.07       0
  4998.9    0.07       0
Bank Sta=4993.7,4998.9
Exp/Cntr=0.3,0.1

Type RM Length L Ch R = 1,753,235,235,235
BEGIN DESCRIPTION:
Elm 01 25 753.35
END DESCRIPTION:
XS GIS Cut Line= 3
      1534816.91      6806996.35      1535040.47      6806774.96
      1535320.23      6806473.51
#Sta/Elev= 30
  4684.7 1948.99  4837.7 1947.98  4929.7 1945.69  4936.7 1945.33  4943.8 1944.04
  4950.9 1941.32  4962.6 1938.83  4969.5 1937.91  4969.9 1937.41  4974.3 1937.41
  4974.7 1937.91  4986.3 1938.87  5028.7 1940.20  5078.0 1939.61  5127.9 1940.71
  5156.2 1941.85  5163.0 1942.83  5170.4 1942.32  5212.9 1942.19  5262.2 1942.90
  5283.2 1942.33  5304.8 1943.29  5311.6 1944.84  5333.1 1947.21  5354.1 1954.55
  5361.4 1957.98  5368.3 1956.85  5375.6 1957.47  5382.4 1957.04  5410.6 1958.10
#Mann=4,-1,0
  4684.7   0.035       0  4962.6    0.07       0  4969.5    0.07       0
  4974.7    0.07       0
Bank Sta=4969.5,4974.7
Exp/Cntr=0.3,0.1

Type RM Length L Ch R = 1,518,147,147,147
BEGIN DESCRIPTION:
Elm 01 25 517.611
END DESCRIPTION:
XS GIS Cut Line= 3
      1535012.03      6807085.30      1535254.04      6806838.87
      1535446.96      6806639.95
#Sta/Elev= 30
  4654.6 1946.42  4690.2 1946.28  4775.1 1943.48  4866.9 1941.98  4895.2 1940.65
  4903.1 1940.83  4909.4 1939.51  4923.5 1938.51  4980.1 1938.38  5008.4 1937.80
  5019.9 1935.49  5020.3 1934.99  5024.7 1934.99  5025.1 1935.49  5036.7 1939.37
  5043.6 1940.22  5079.1 1940.82  5111.7 1942.18  5118.2 1943.10  5128.5 1944.72
  5135.7 1944.01  5149.8 1945.61  5156.8 1945.20  5178.1 1946.68  5192.3 1947.05
  5220.6 1949.25  5234.7 1949.96  5241.7 1949.67  5248.9 1950.76  5277.1 1951.75
#Mann=6,-1,0
  4654.6   0.035       0  4903.1    0.07       0  5019.9    0.07       0
  5025.1    0.07       0  5111.7   0.035       0  5118.2    0.07       0
Bank Sta=5019.9,5025.1
Exp/Cntr=0.3,0.1

Type RM Length L Ch R = 1,371,136,136,136
BEGIN DESCRIPTION:
Elm 01 25 370.508
END DESCRIPTION:
XS GIS Cut Line= 3
      1535056.29      6807163.02      1535327.72      6806960.26
      1535525.09      6806754.53
#Sta/Elev= 30
  4661.2 1945.43  4721.9 1945.56  4828.2 1941.74  4892.8 1941.19  4899.1 1940.44
  4912.0 1940.23  4928.3 1939.79  4942.9 1940.02  4957.5 1939.05  4971.6 1937.37
  4978.2 1937.35  4992.9 1937.69  5004.1 1936.40  5004.5 1935.90  5008.9 1935.90
  5009.3 1936.40  5035.0 1937.35  5057.2 1937.54  5070.5 1937.69  5119.9 1940.06
  5141.3 1940.13  5197.6 1943.31  5204.8 1943.22  5211.7 1944.09  5246.2 1944.72
  5261.4 1945.89  5268.3 1949.33  5275.6 1948.90  5281.4 1950.37  5285.1 1950.37
#Mann=7,-1,0
  4661.2   0.035       0  4912.0    0.07       0  4978.2   0.035       0
  5004.1   0.035       0  5009.3   0.035       0  5057.2    0.07       0
  5246.2    0.16       0
Bank Sta=5004.1,5009.3
Exp/Cntr=0.3,0.1

Type RM Length L Ch R = 1,235,0,0,0
BEGIN DESCRIPTION:
Elm 01 25 235.407
END DESCRIPTION:
XS GIS Cut Line= 3
      1535157.90      6807176.42      1535391.33      6807074.77
      1535597.94      6806963.02
#Sta/Elev= 30
  4745.4 1945.05  4783.3 1944.43  4884.3 1941.10  4916.7 1941.30  4925.8 1940.68
  4931.2 1939.81  4949.2 1939.43  4960.4 1938.28  4971.3 1936.15  4975.5 1936.01
  4975.9 1935.51  4980.3 1935.51  4980.7 1936.01  5002.6 1936.80  5028.7 1936.17
  5050.6 1936.66  5082.9 1936.10  5088.6 1936.73  5095.5 1936.58  5110.5 1937.68
  5126.7 1937.04  5132.4 1938.33  5140.6 1937.59  5154.3 1937.75  5170.5 1937.23
  5186.1 1941.28  5192.3 1944.14  5198.6 1946.36  5207.6 1946.11  5234.9 1944.96
#Mann=8,-1,0
  4745.4   0.035       0  4783.3    0.07       0  4975.5    0.07       0
  4980.7    0.07       0  5002.6   0.035       0  5095.5    0.16       0
  5198.6    0.07       0  5207.6    0.16       0
Bank Sta=4975.5,4980.7
Exp/Cntr=0.3,0.1

Chan Stop Cuts=-1