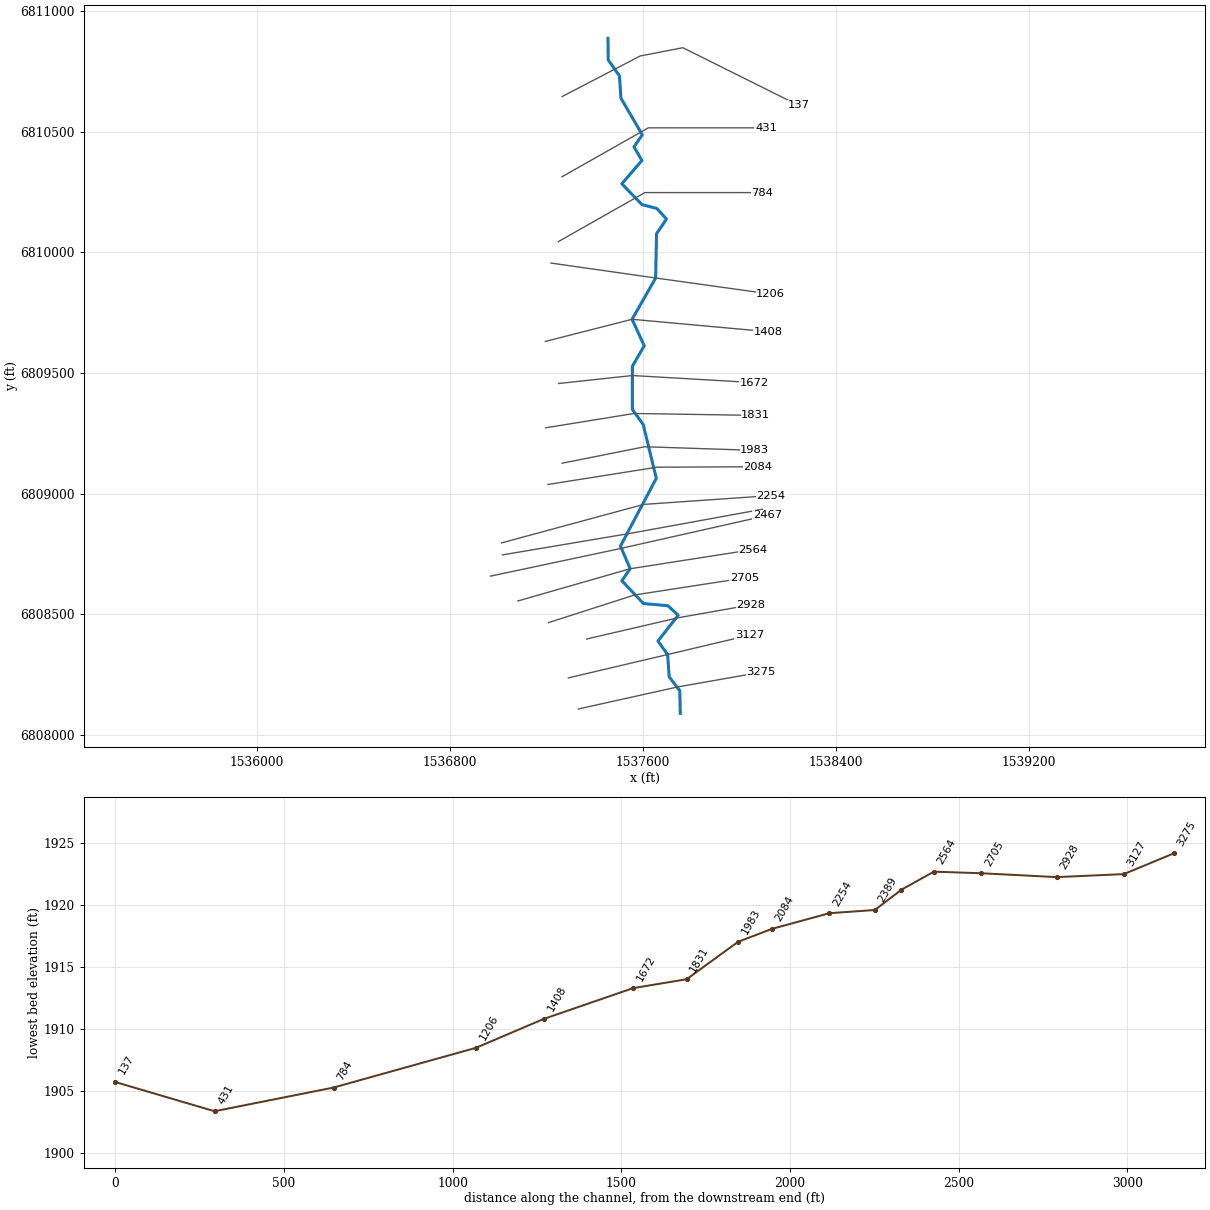
--- Elm 01 26.prj (project) ---

Proj Title=Elm 01 26 Base Level Engineering
Current Plan=p01
Default Exp/Contr=0.3,0.1
English Units
Geom File=g01
Flow File=f01
Plan File=p01
BEGIN DESCRIPTION:
Elm 01 26
END DESCRIPTION:

--- Elm 01 26.p01 (plan) ---

Plan Title=Multiple Run
Short Identifier=Multiple
Geom File=g01
Flow File=f01
Subcritical Flow
K Sum by GR= 0
Std Step Tol= 0.01
Critical Tol= 0.01
Num of Std Step Trials= 20
Max Error Tol= 0.3
Flow Tol Ratio= 0.001
Split Flow NTrial= 30
Split Flow Tol= 0.02
Split Flow Ratio= 0.02
Log Output Level= 0
Friction Slope Method= 1
Unsteady Friction Slope Method= 2
Unsteady Bridges Friction Slope Method= 1
Parabolic Critical Depth
Global Vel Dist=  1 , 1 , 1
Global Log Level= 0
CheckData=True
Encroach Param= -1, 0, 0, 0
BEGIN DESCRIPTION:
Multiple Run
END DESCRIPTION:

--- Elm 01 26.f01 (steady flow) ---

Flow Title=Multiple
Number of Profiles=7
Profile Names=10-year,25-year,50-year,1pct_min,100-year,1pct_plu,500-year
River Rch & RM= Elm 01 26,Reach-1,3275
     172     234     284     214     342     471     505
Boundary for River Rch & Prof#=Elm 01 26,Reach-1,1
Up Type=0
Dn Type=3
Dn Slope=0.005
Boundary for River Rch & Prof#=Elm 01 26,Reach-1,2
Up Type=0
Dn Type=3
Dn Slope=0.005
Boundary for River Rch & Prof#=Elm 01 26,Reach-1,3
Up Type=0
Dn Type=3
Dn Slope=0.005
Boundary for River Rch & Prof#=Elm 01 26,Reach-1,4
Up Type=0
Dn Type=3
Dn Slope=0.005
Boundary for River Rch & Prof#=Elm 01 26,Reach-1,5
Up Type=0
Dn Type=3
Dn Slope=0.005
Boundary for River Rch & Prof#=Elm 01 26,Reach-1,6
Up Type=0
Dn Type=3
Dn Slope=0.005
Boundary for River Rch & Prof#=Elm 01 26,Reach-1,7
Up Type=0
Dn Type=3
Dn Slope=0.005

--- Elm 01 26.g01 (geometry) ---

Geom Title=Existing Conditions

River Reach=Elm 01 26,Reach-1
Reach XY= 30
      1537755.00      6808088.00      1537752.90      6808182.13
      1537708.82      6808239.59      1537702.44      6808332.11
      1537662.34      6808388.10      1537746.17      6808494.99
      1537703.99      6808534.39      1537602.55      6808543.52
      1537512.54      6808637.98      1537547.16      6808687.91
      1537506.84      6808781.87      1537655.41      6809063.00
      1537601.14      6809286.40      1537556.22      6809348.50
      1537556.24      6809527.50      1537605.39      6809613.00
      1537555.08      6809722.61      1537652.76      6809893.93
      1537656.39      6810077.57      1537697.77      6810138.32
      1537657.85      6810182.15      1537595.31      6810198.78
      1537512.60      6810284.65      1537595.67      6810381.33
      1537563.04      6810438.00      1537597.25      6810487.91
      1537508.83      6810639.58      1537502.67      6810732.03
      1537456.02      6810798.42      1537455.00      6810888.00

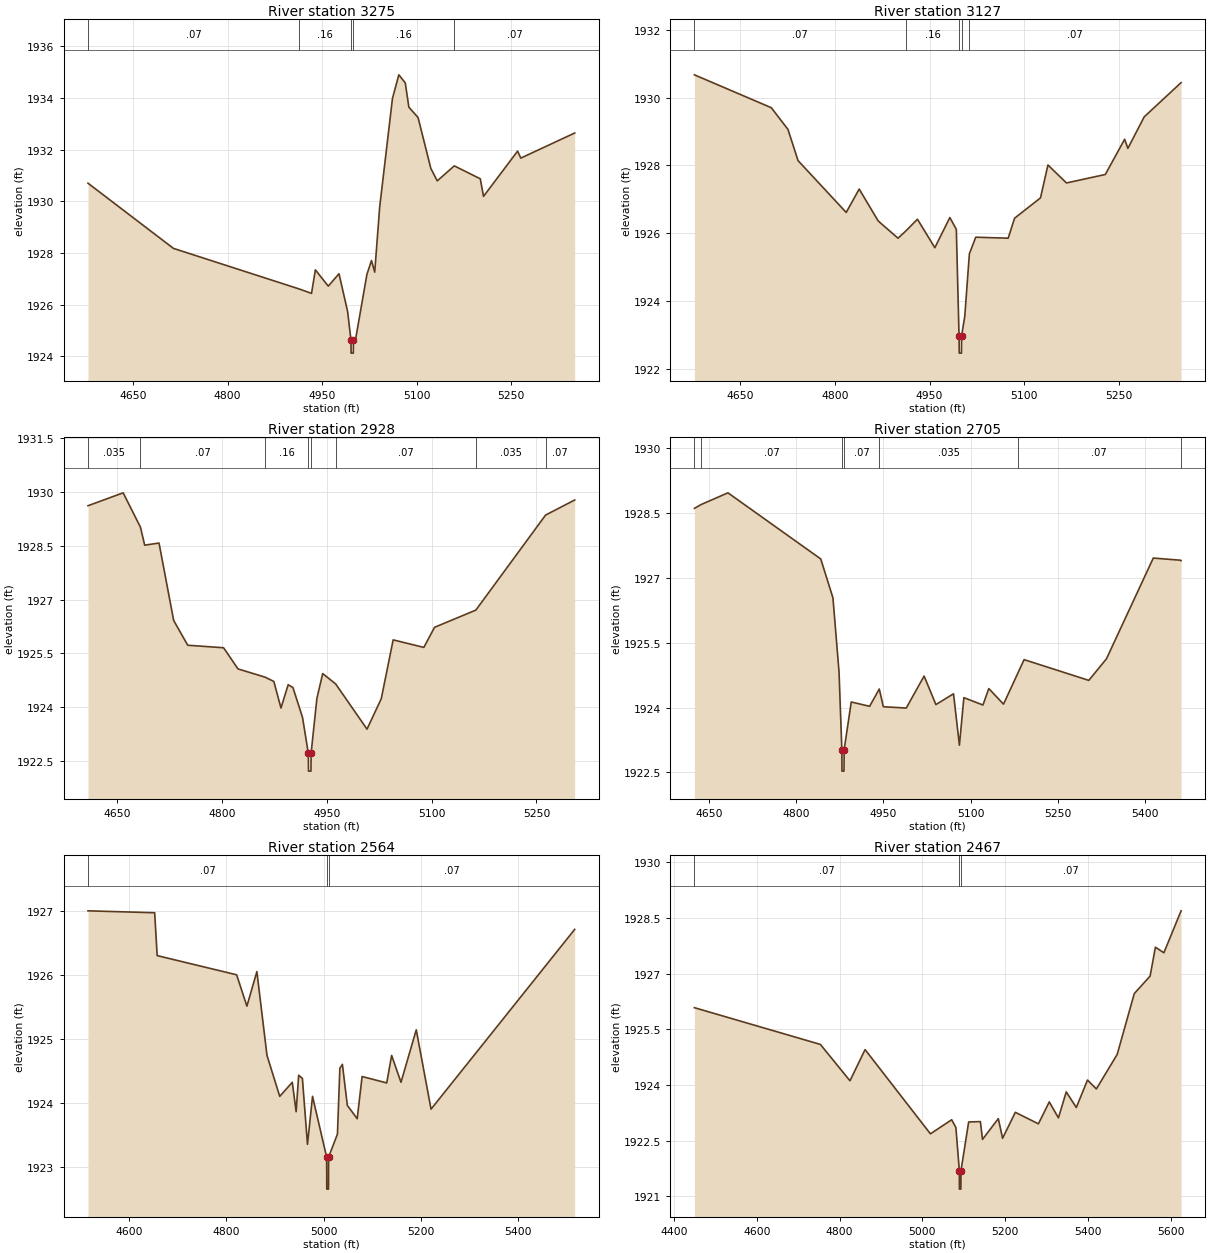
Type RM Length L Ch R = 1,3275,148,148,148
BEGIN DESCRIPTION:
Elm 01 26 3274.922
END DESCRIPTION:
XS GIS Cut Line= 3
      1537332.66      6808106.32      1537744.15      6808197.65
      1538089.81      6808258.62
#Sta/Elev= 30
  4578.5 1930.70  4714.1 1928.18  4913.8 1926.61  4933.3 1926.44  4939.4 1927.35
  4959.9 1926.72  4976.9 1927.20  4990.6 1925.74  4995.9 1924.63  4996.1 1924.13
  4999.6 1924.13  4999.9 1924.63  5003.0 1924.63  5021.2 1927.17  5028.5 1927.71
  5033.6 1927.26  5041.5 1929.78  5061.8 1933.98  5071.9 1934.89  5082.1 1934.58
  5087.8 1933.64  5102.4 1933.24  5122.7 1931.27  5132.9 1930.79  5159.9 1931.37
  5201.2 1930.87  5206.3 1930.19  5260.4 1931.94  5265.5 1931.67  5351.0 1932.64
#Mann=5,-1,0
  4578.5    0.07       0  4913.8    0.16       0  4995.9    0.07       0
  4999.9    0.16       0  5159.9    0.07       0
Bank Sta=4995.9,4999.9
Exp/Cntr=0.3,0.1

Type RM Length L Ch R = 1,3127,199,199,199
BEGIN DESCRIPTION:
Elm 01 26 3127.166
END DESCRIPTION:
XS GIS Cut Line= 3
      1537290.58      6808235.24      1537702.44      6808332.11
      1538041.96      6808412.47
#Sta/Elev= 30
  4576.9 1930.67  4698.9 1929.70  4725.3 1929.06  4741.3 1928.14  4817.7 1926.61
  4838.3 1927.30  4868.4 1926.36  4899.9 1925.85  4912.1 1926.06  4930.7 1926.41
  4958.3 1925.57  4982.1 1926.46  4992.4 1926.11  4996.7 1922.96  4997.0 1922.46
  5000.5 1922.46  5000.7 1922.96  5005.8 1923.55  5013.1 1925.39  5023.2 1925.88
  5074.6 1925.85  5084.8 1926.44  5125.9 1927.04  5137.7 1928.01  5167.1 1927.48
  5228.7 1927.73  5259.4 1928.77  5264.5 1928.50  5290.4 1929.43  5348.9 1930.44
#Mann=5,-1,0
  4576.9    0.07       0  4912.1    0.16       0  4996.7    0.07       0
  5000.7    0.16       0  5013.1    0.07       0
Bank Sta=4996.7,5000.7
Exp/Cntr=0.3,0.1

Type RM Length L Ch R = 1,2928,223,223,223
BEGIN DESCRIPTION:
Elm 01 26 2927.926
END DESCRIPTION:
XS GIS Cut Line= 3
      1537366.00      6808396.38      1537747.47      6808484.87
      1538047.53      6808537.83
#Sta/Elev= 30
  4608.4 1929.62  4658.7 1929.98  4683.5 1929.02  4689.5 1928.52  4710.0 1928.58
  4731.0 1926.42  4751.1 1925.73  4802.4 1925.66  4823.0 1925.07  4861.8 1924.84
  4874.3 1924.72  4884.5 1923.98  4894.8 1924.63  4901.6 1924.55  4915.3 1923.72
  4923.6 1922.72  4923.9 1922.22  4927.4 1922.22  4927.6 1922.72  4935.9 1924.25
  4944.2 1924.94  4962.8 1924.65  5007.6 1923.39  5028.0 1924.24  5045.0 1925.88
  5088.9 1925.67  5104.2 1926.23  5163.3 1926.71  5263.1 1929.36  5304.7 1929.78
#Mann=8,-1,0
  4608.4   0.035       0  4683.5    0.07       0  4861.8    0.16       0
  4923.6    0.07       0  4927.6    0.16       0  4962.8    0.07       0
  5163.3   0.035       0  5263.1    0.07       0
Bank Sta=4923.6,4927.6
Exp/Cntr=0.3,0.1

Type RM Length L Ch R = 1,2705,141,141,141
BEGIN DESCRIPTION:
Elm 01 26 2705.461
END DESCRIPTION:
XS GIS Cut Line= 3
      1537208.10      6808464.36      1537565.02      6808579.07
      1538021.81      6808649.59
#Sta/Elev= 30
  4625.1 1928.61  4636.8 1928.70  4682.8 1928.97  4842.4 1927.44  4863.4 1926.54
  4873.9 1924.82  4878.7 1923.03  4878.9 1922.53  4882.4 1922.53  4882.7 1923.03
  4894.9 1924.13  4926.5 1924.03  4943.1 1924.43  4950.1 1924.02  4989.5 1923.99
  5020.2 1924.73  5040.5 1924.07  5070.8 1924.32  5080.9 1923.13  5088.6 1924.23
  5121.4 1924.06  5131.5 1924.44  5156.8 1924.08  5181.2 1924.79  5192.2 1925.11
  5303.5 1924.63  5333.9 1925.13  5414.4 1927.46  5461.7 1927.41  5462.2 1927.40
#Mann=7,-1,0
  4625.1   0.035       0  4636.8    0.07       0  4878.7   0.035       0
  4882.7    0.07       0  4943.1   0.035       0  5181.2    0.07       0
  5461.7   0.035       0
Bank Sta=4878.7,4882.7
Exp/Cntr=0.3,0.1

Type RM Length L Ch R = 1,2564,97,97,97
BEGIN DESCRIPTION:
Elm 01 26 2564.179
END DESCRIPTION:
XS GIS Cut Line= 3
      1537081.33      6808554.36      1537547.16      6808687.91
      1538056.69      6808767.44
#Sta/Elev= 30
  4515.4 1927.01  4652.4 1926.98  4657.6 1926.31  4820.9 1926.01  4842.0 1925.52
  4862.5 1926.06  4883.3 1924.75  4909.5 1924.11  4935.3 1924.33  4943.2 1923.87
  4948.4 1924.44  4956.1 1924.39  4966.5 1923.36  4976.9 1924.11  5005.9 1923.16
  5006.2 1922.66  5009.7 1922.66  5009.9 1923.16  5028.1 1923.52  5033.1 1924.55
  5038.3 1924.61  5048.4 1923.97  5068.7 1923.76  5078.8 1924.42  5129.4 1924.32
  5139.5 1924.75  5158.7 1924.33  5190.1 1925.15  5220.5 1923.91  5515.7 1926.72
#Mann=3,-1,0
  4515.4    0.07       0  5005.9    0.07       0  5009.9    0.07       0
Bank Sta=5005.9,5009.9
Exp/Cntr=0.3,0.1

Type RM Length L Ch R = 1,2467,78,78,78
BEGIN DESCRIPTION:
Elm 01 26 2466.89
END DESCRIPTION:
XS GIS Cut Line= 3
      1536967.47      6808657.24      1537503.81      6808771.12
      1538115.49      6808908.88
#Sta/Elev= 30
  4449.5 1926.08  4753.7 1925.09  4825.2 1924.11  4861.7 1924.95  5019.5 1922.68
  5070.8 1923.06  5081.0 1922.85  5089.3 1921.69  5089.5 1921.19  5093.0 1921.19
  5093.3 1921.69  5111.8 1923.00  5140.1 1923.01  5145.3 1922.53  5183.4 1923.09
  5193.8 1922.56  5224.5 1923.26  5280.2 1922.95  5306.5 1923.54  5328.6 1923.11
  5347.5 1923.81  5371.8 1923.39  5398.8 1924.13  5420.2 1923.89  5470.5 1924.82
  5511.8 1926.46  5550.0 1926.93  5562.8 1927.71  5583.3 1927.56  5624.8 1928.69
#Mann=3,-1,0
  4449.5    0.07       0  5089.3    0.07       0  5093.3    0.07       0
Bank Sta=5089.3,5093.3
Exp/Cntr=0.3,0.1

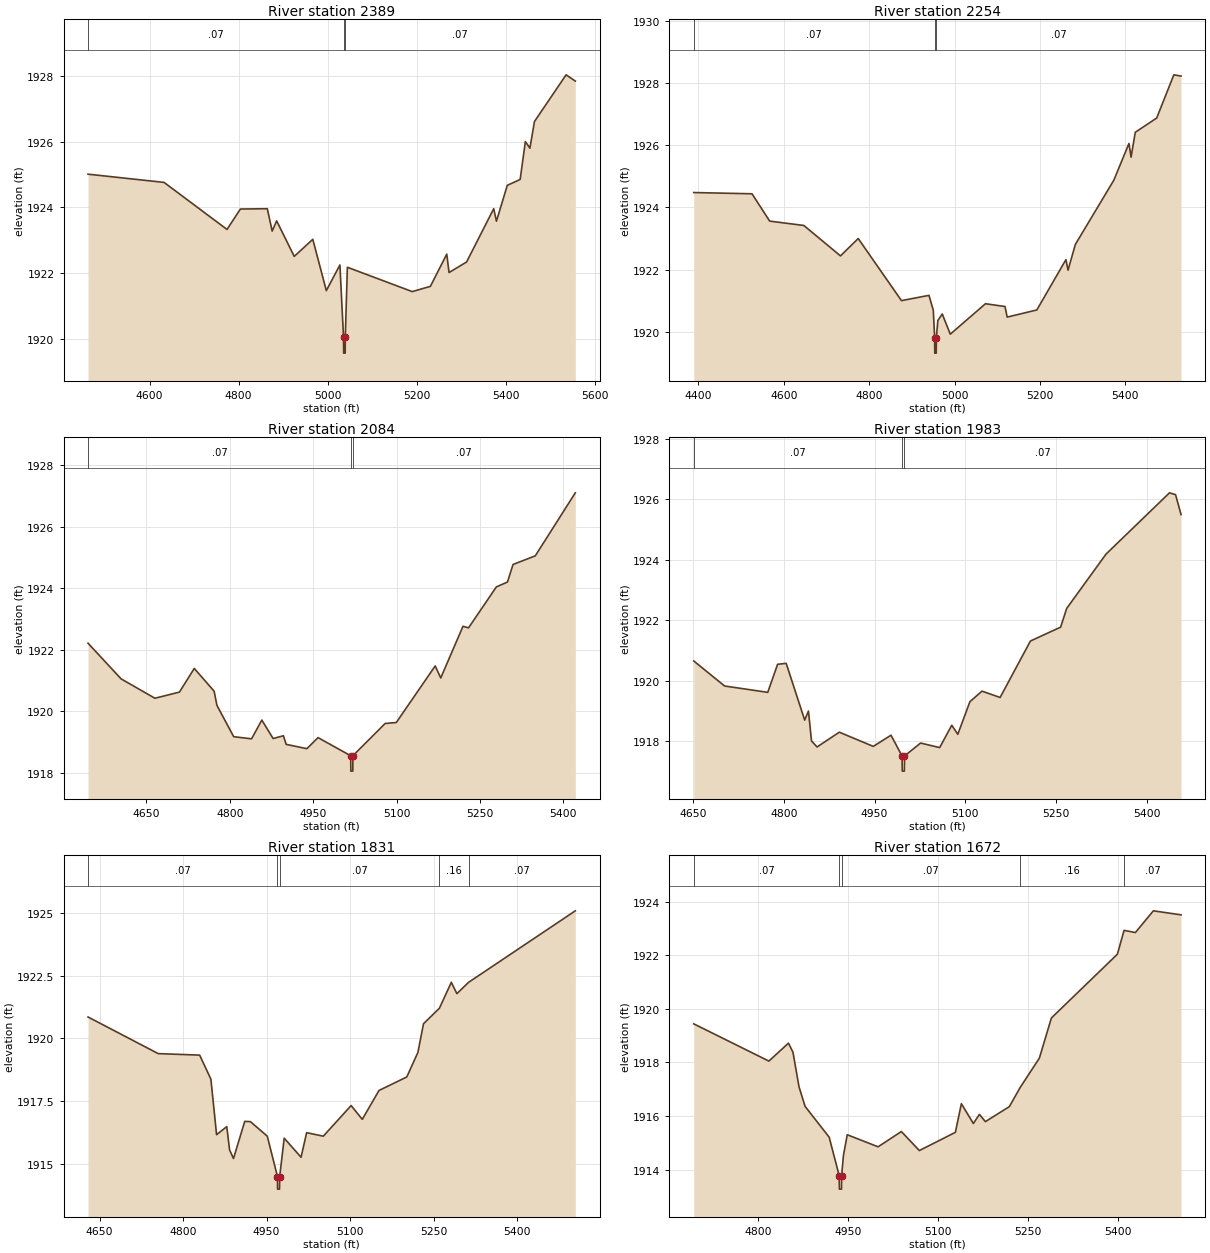
Type RM Length L Ch R = 1,2389,135,135,135
BEGIN DESCRIPTION:
Elm 01 26 2389.26
END DESCRIPTION:
XS GIS Cut Line= 3
      1537017.05      6808745.40      1537551.57      6808835.41
      1538095.35      6808934.61
#Sta/Elev= 30
  4461.6 1925.01  4632.4 1924.76  4773.9 1923.33  4803.9 1923.95  4864.4 1923.96
  4875.3 1923.28  4885.4 1923.59  4924.9 1922.51  4966.6 1923.03  4997.0 1921.47
  5027.5 1922.25  5035.6 1920.07  5035.9 1919.57  5039.4 1919.57  5039.6 1920.07
  5044.3 1922.18  5190.1 1921.44  5230.8 1921.60  5267.6 1922.58  5272.7 1922.02
  5312.1 1922.34  5373.1 1923.96  5379.2 1923.58  5403.6 1924.67  5432.5 1924.85
  5444.2 1926.00  5454.4 1925.80  5464.6 1926.61  5535.7 1928.03  5556.4 1927.84
#Mann=3,-1,0
  4461.6    0.07       0  5035.6    0.07       0  5039.6    0.07       0
Bank Sta=5035.6,5039.6
Exp/Cntr=0.3,0.1

Type RM Length L Ch R = 1,2254,170,170,170
BEGIN DESCRIPTION:
Elm 01 26 2253.57
END DESCRIPTION:
XS GIS Cut Line= 3
      1537013.34      6808794.99      1537603.01      6808954.81
      1538131.90      6808991.41
#Sta/Elev= 30
  4389.3 1924.48  4525.7 1924.44  4567.1 1923.56  4647.1 1923.42  4732.9 1922.44
  4774.4 1923.00  4875.7 1921.00  4940.1 1921.17  4950.2 1920.69  4953.4 1919.81
  4953.6 1919.31  4957.1 1919.31  4957.4 1919.81  4960.9 1920.36  4971.2 1920.57
  4990.0 1919.92  5072.4 1920.90  5118.2 1920.81  5123.2 1920.47  5192.7 1920.70
  5260.8 1922.32  5265.8 1921.98  5282.9 1922.81  5373.1 1924.88  5408.4 1926.06
  5413.4 1925.62  5423.2 1926.42  5473.4 1926.88  5513.5 1928.27  5530.4 1928.23
#Mann=3,-1,0
  4389.3    0.07       0  4953.4    0.07       0  4957.4    0.07       0
Bank Sta=4953.4,4957.4
Exp/Cntr=0.3,0.1

Type RM Length L Ch R = 1,2084,101,101,101
BEGIN DESCRIPTION:
Elm 01 26 2084.06
END DESCRIPTION:
XS GIS Cut Line= 3
      1537206.21      6809037.47      1537658.11      6809109.11
      1538076.97      6809110.95
#Sta/Elev= 30
  4545.2 1922.21  4604.7 1921.05  4665.5 1920.42  4709.6 1920.62  4736.3 1921.39
  4772.0 1920.65  4777.0 1920.19  4807.2 1919.17  4839.3 1919.10  4857.8 1919.71
  4878.1 1919.11  4896.6 1919.20  4901.6 1918.92  4938.8 1918.78  4958.9 1919.14
  5017.6 1918.55  5017.9 1918.05  5021.4 1918.05  5021.6 1918.55  5079.6 1919.60
  5099.6 1919.63  5169.6 1921.47  5179.6 1921.08  5219.6 1922.76  5229.6 1922.71
  5279.6 1924.04  5299.6 1924.20  5309.6 1924.77  5349.6 1925.05  5421.6 1927.10
#Mann=3,-1,0
  4545.2    0.07       0  5017.6    0.07       0  5021.6    0.07       0
Bank Sta=5017.6,5021.6
Exp/Cntr=0.3,0.1

Type RM Length L Ch R = 1,1983,152,152,152
BEGIN DESCRIPTION:
Elm 01 26 1983.289
END DESCRIPTION:
XS GIS Cut Line= 3
      1537265.01      6809125.64      1537607.36      6809193.97
      1538064.11      6809178.91
#Sta/Elev= 30
  4650.9 1920.65  4701.9 1919.82  4773.3 1919.61  4789.6 1920.54  4803.8 1920.57
  4834.4 1918.69  4840.6 1918.99  4845.7 1918.00  4854.8 1917.80  4891.7 1918.29
  4947.8 1917.82  4977.2 1918.19  4995.5 1917.50  4995.8 1917.00  4999.3 1917.00
  4999.5 1917.50  5026.1 1917.93  5057.7 1917.78  5077.7 1918.52  5087.7 1918.22
  5107.7 1919.30  5127.7 1919.65  5157.7 1919.44  5207.8 1921.31  5257.8 1921.77
  5267.8 1922.39  5332.9 1924.19  5437.9 1926.22  5447.9 1926.16  5457.0 1925.50
#Mann=3,-1,0
  4650.9    0.07       0  4995.5    0.07       0  4999.5    0.07       0
Bank Sta=4995.5,4999.5
Exp/Cntr=0.3,0.1

Type RM Length L Ch R = 1,1831,159,159,159
BEGIN DESCRIPTION:
Elm 01 26 1831.15
END DESCRIPTION:
XS GIS Cut Line= 3
      1537197.02      6809272.59      1537563.14      6809331.94
      1538067.77      6809324.03
#Sta/Elev= 30
  4629.1 1920.85  4755.2 1919.39  4829.7 1919.33  4849.9 1918.37  4860.1 1916.16
  4878.4 1916.48  4883.5 1915.55  4890.5 1915.21  4910.7 1916.69  4920.8 1916.68
  4951.2 1916.10  4969.5 1914.49  4969.7 1913.99  4973.2 1913.99  4973.5 1914.49
  4981.6 1916.02  5011.9 1915.26  5021.9 1916.24  5051.9 1916.10  5101.9 1917.32
  5121.9 1916.77  5151.9 1917.92  5201.9 1918.46  5221.9 1919.44  5231.9 1920.58
  5260.5 1921.20  5281.9 1922.23  5291.9 1921.78  5312.9 1922.23  5504.7 1925.08
#Mann=5,-1,0
  4629.1    0.07       0  4969.5    0.07       0  4973.5    0.07       0
  5260.5    0.16       0  5312.9    0.07       0
Bank Sta=4969.5,4973.5
Exp/Cntr=0.3,0.1

Type RM Length L Ch R = 1,1672,264,264,264
BEGIN DESCRIPTION:
Elm 01 26 1672.349
END DESCRIPTION:
XS GIS Cut Line= 3
      1537250.31      6809456.29      1537556.23      6809489.36
      1538061.08      6809460.03
#Sta/Elev= 30
  4692.3 1919.44  4817.7 1918.05  4850.4 1918.72  4857.9 1918.38  4868.0 1917.09
  4878.1 1916.36  4918.3 1915.21  4935.1 1913.77  4935.4 1913.27  4938.9 1913.27
  4939.1 1913.77  4942.2 1914.54  4948.5 1915.30  5000.0 1914.85  5038.8 1915.42
  5068.9 1914.71  5129.0 1915.39  5139.0 1916.46  5159.0 1915.72  5169.1 1916.06
  5179.1 1915.79  5219.1 1916.35  5237.3 1917.07  5269.2 1918.16  5289.3 1919.66
  5399.4 1922.04  5410.6 1922.93  5429.5 1922.85  5459.5 1923.66  5505.7 1923.51
#Mann=5,-1,0
  4692.3    0.07       0  4935.1    0.07       0  4939.1    0.07       0
  5237.3    0.16       0  5410.6    0.07       0
Bank Sta=4935.1,4939.1
Exp/Cntr=0.3,0.1

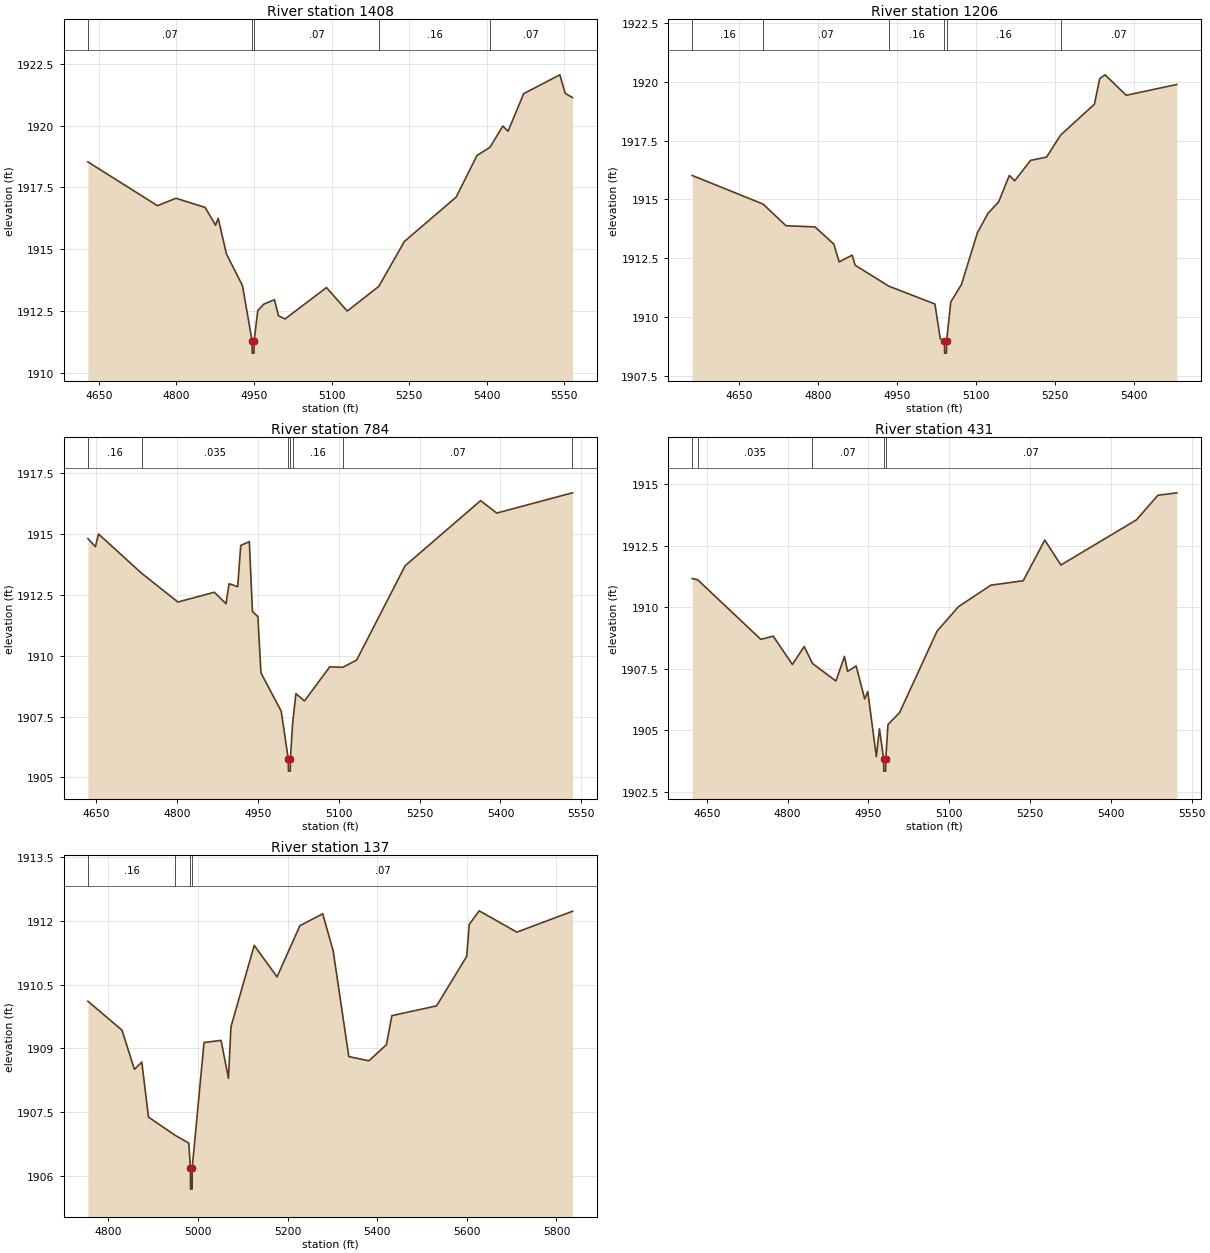
Type RM Length L Ch R = 1,1408,202,202,202
BEGIN DESCRIPTION:
Elm 01 26 1407.76
END DESCRIPTION:
XS GIS Cut Line= 3
      1537195.21      6809630.80      1537555.08      6809722.61
      1538119.15      6809671.21
#Sta/Elev= 30
  4628.6 1918.53  4763.3 1916.76  4799.0 1917.06  4855.4 1916.69  4875.6 1915.97
  4880.7 1916.25  4896.7 1914.81  4927.7 1913.53  4946.3 1911.30  4946.6 1910.80
  4950.1 1910.80  4950.3 1911.30  4957.3 1912.52  4969.0 1912.78  4989.6 1912.96
  4997.4 1912.31  5010.0 1912.18  5090.3 1913.45  5130.5 1912.50  5191.6 1913.50
  5240.9 1915.31  5341.3 1917.11  5381.5 1918.79  5406.6 1919.12  5431.6 1919.98
  5441.7 1919.77  5471.9 1921.29  5541.9 1922.05  5552.2 1921.30  5566.4 1921.13
#Mann=5,-1,0
  4628.6    0.07       0  4946.3    0.07       0  4950.3    0.07       0
  5191.6    0.16       0  5406.6    0.07       0
Bank Sta=4946.3,4950.3
Exp/Cntr=0.3,0.1

Type RM Length L Ch R = 1,1206,422,422,422
BEGIN DESCRIPTION:
Elm 01 26 1205.786
END DESCRIPTION:
XS GIS Cut Line= 3
      1537218.66      6809955.87      1537652.76      6809893.93
      1538130.04      6809827.34
#Sta/Elev= 30
  4561.5 1916.02  4696.2 1914.80  4739.6 1913.88  4794.7 1913.83  4830.5 1913.10
  4840.6 1912.34  4865.4 1912.63  4870.9 1912.20  4934.9 1911.31  5022.5 1910.55
  5032.6 1909.08  5040.6 1908.96  5040.9 1908.46  5044.4 1908.46  5044.6 1908.96
  5052.7 1910.64  5072.9 1911.38  5103.2 1913.58  5123.4 1914.41  5143.6 1914.90
  5163.8 1916.02  5173.9 1915.79  5204.2 1916.66  5234.5 1916.80  5261.4 1917.74
  5325.4 1919.05  5335.5 1920.14  5345.6 1920.30  5385.9 1919.43  5481.9 1919.89
#Mann=6,-1,0
  4561.5    0.16       0  4696.2    0.07       0  4934.9    0.16       0
  5040.6    0.07       0  5044.6    0.16       0  5261.4    0.07       0
Bank Sta=5040.6,5044.6
Exp/Cntr=0.3,0.1

Type RM Length L Ch R = 1,784,353,353,353
BEGIN DESCRIPTION:
Elm 01 26 1.0
END DESCRIPTION:
XS GIS Cut Line= 3
      1537249.70      6810045.06      1537608.16      6810248.23
      1538095.63      6810248.16
#Sta/Elev= 30
  4634.3 1914.80  4648.3 1914.47  4654.0 1914.99  4734.0 1913.38  4801.3 1912.20
  4869.0 1912.60  4890.6 1912.13  4896.4 1912.95  4912.3 1912.83  4918.0 1914.52
  4933.9 1914.68  4939.7 1911.81  4949.8 1911.60  4955.5 1909.29  4993.1 1907.72
  5006.2 1905.76  5006.5 1905.26  5010.0 1905.26  5010.2 1905.76  5014.2 1907.21
  5020.4 1908.44  5036.3 1908.14  5083.2 1909.54  5107.5 1909.52  5133.2 1909.82
  5223.2 1913.69  5363.2 1916.36  5393.2 1915.85  5533.6 1916.68  5533.8 1916.68
#Mann=7,-1,0
  4634.3    0.16       0  4734.0   0.035       0  5006.2   0.035       0
  5010.2   0.035       0  5014.2    0.16       0  5107.5    0.07       0
  5533.6   0.035       0
Bank Sta=5006.2,5010.2
Exp/Cntr=0.3,0.1

Type RM Length L Ch R = 1,431,294,294,294
BEGIN DESCRIPTION:
Elm 01 26 702.737
END DESCRIPTION:
XS GIS Cut Line= 3
      1537264.13      6810313.61      1537622.59      6810516.78
      1538110.06      6810516.71
#Sta/Elev= 30
  4623.0 1911.17  4633.2 1911.12  4750.4 1908.70  4773.4 1908.83  4809.0 1907.68
  4830.9 1908.41  4846.3 1907.72  4889.8 1907.01  4905.7 1908.01  4911.4 1907.40
  4927.3 1907.62  4943.2 1906.28  4948.9 1906.58  4964.8 1903.94  4970.6 1905.07
  4978.3 1903.85  4978.6 1903.35  4982.1 1903.35  4982.3 1903.85  4986.4 1905.24
  5008.1 1905.73  5077.4 1909.03  5117.4 1910.03  5177.4 1910.90  5237.4 1911.08
  5277.4 1912.73  5307.4 1911.72  5447.4 1913.55  5487.4 1914.55  5522.5 1914.65
#Mann=5,-1,0
  4623.0    0.16       0  4633.2   0.035       0  4846.3    0.07       0
  4978.3    0.07       0  4982.3    0.07       0
Bank Sta=4978.3,4982.3
Exp/Cntr=0.3,0.1

Type RM Length L Ch R = 1,137,0,0,0
BEGIN DESCRIPTION:
Elm 01 26 171.57
END DESCRIPTION:
XS GIS Cut Line= 4
      1537265.02      6810646.62      1537588.53      6810814.76
      1537765.52      6810849.20      1538245.90      6810609.89
#Sta/Elev= 30
  4754.3 1910.11  4830.4 1909.43  4858.1 1908.51  4874.6 1908.68  4889.5 1907.39
  4949.5 1906.96  4979.5 1906.78  4983.1 1906.20  4983.4 1905.70  4986.9 1905.70
  4987.1 1906.20  5013.5 1909.14  5051.5 1909.19  5068.0 1908.30  5073.6 1909.51
  5125.5 1911.42  5176.4 1910.68  5227.4 1911.88  5278.3 1912.16  5301.7 1911.29
  5336.6 1908.81  5381.4 1908.71  5420.6 1909.09  5432.7 1909.77  5532.5 1910.00
  5599.7 1911.16  5605.3 1911.91  5627.6 1912.23  5711.6 1911.73  5835.9 1912.22
#Mann=4,-1,0
  4754.3    0.16       0  4949.5    0.07       0  4983.1    0.07       0
  4987.1    0.07       0
Bank Sta=4983.1,4987.1
Exp/Cntr=0.3,0.1

Chan Stop Cuts=-1