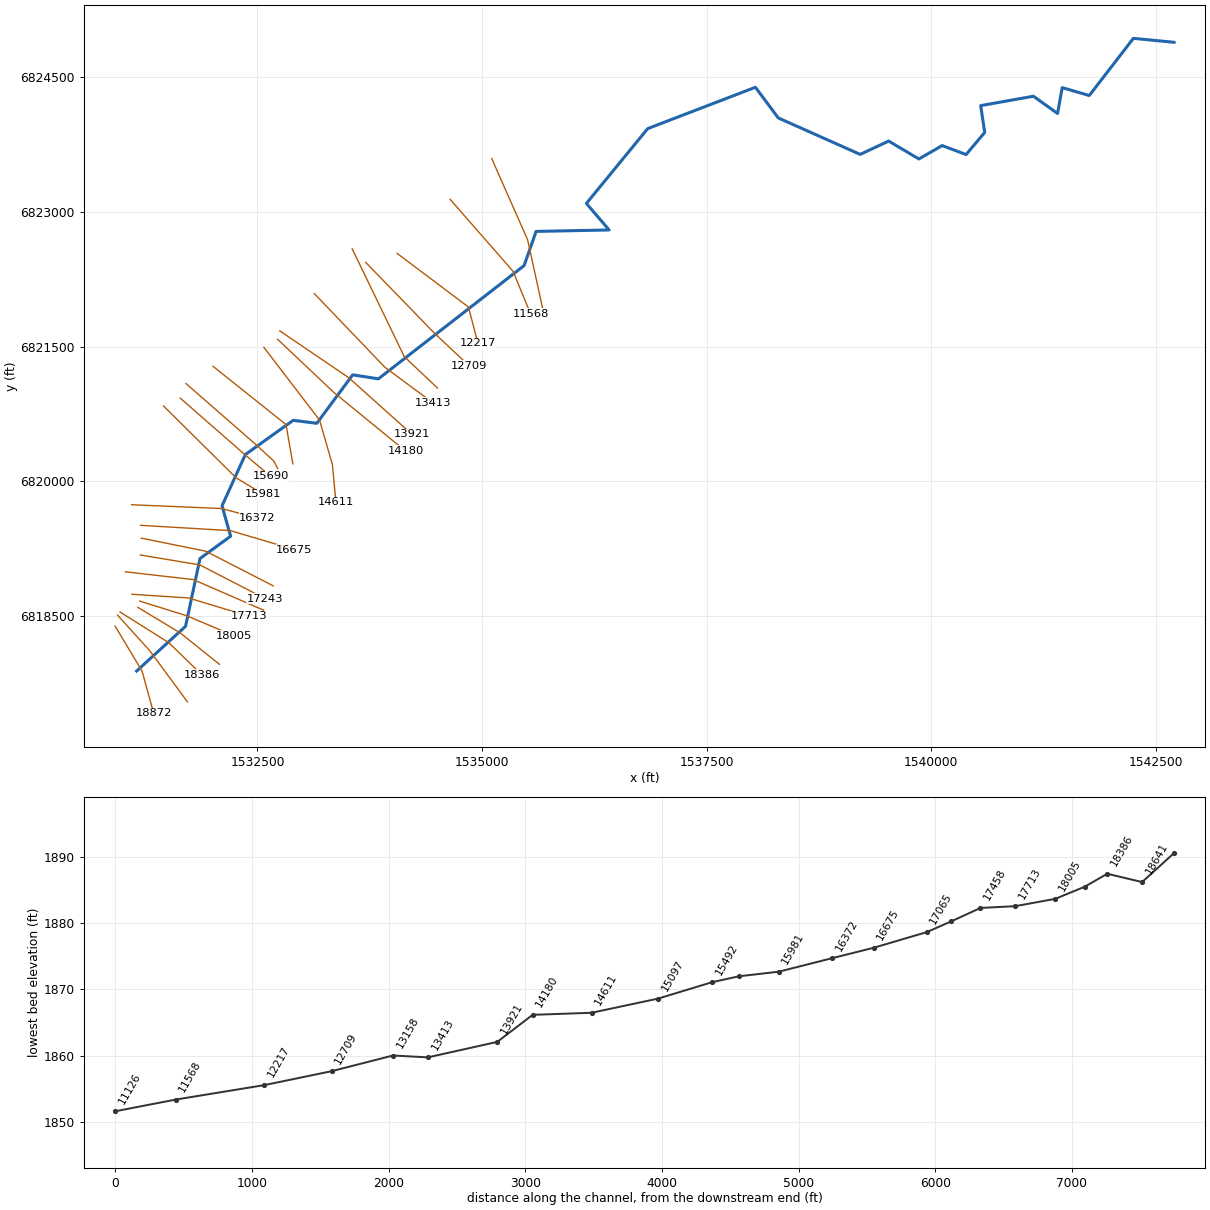
--- Elm 01 27.prj (project) ---

Proj Title=Elm 01 27 Base Level Engineering
Current Plan=p01
Default Exp/Contr=0.3,0.1
English Units
Geom File=g01
Flow File=f01
Plan File=p01
Y Axis Title=Elevation
X Axis Title(PF)=Main Channel Distance
X Axis Title(XS)=Station
BEGIN DESCRIPTION:
Elm 01 27
END DESCRIPTION:
DSS Export Rating Curves= 0
DSS Export Rating Curve Sorted= 0
DSS Export Volume Flow Curves= 0
DXF OffsetX= 0
DXF OffsetY= 0
DXF ScaleX= 1
DXF ScaleY= 10

--- Elm 01 27.p01 (plan) ---

Plan Title=Multiple Run
Program Version=4.10
Short Identifier=Multiple
Geom File=g01
Flow File=f01
Subcritical Flow
K Sum by GR= 0
Std Step Tol= 0.01
Critical Tol= 0.01
Num of Std Step Trials= 20
Max Error Tol= 0.3
Flow Tol Ratio= 0.001
Split Flow NTrial= 30
Split Flow Tol= 0.02
Split Flow Ratio= 0.02
Log Output Level= 0
Friction Slope Method= 1
Unsteady Friction Slope Method= 2
Unsteady Bridges Friction Slope Method= 1
Parabolic Critical Depth
Global Vel Dist= 1 , 1 , 1
Global Log Level= 0
CheckData=True
Encroach Param=-1 ,0,0, 0
BEGIN DESCRIPTION:
Multiple Run
END DESCRIPTION:
Computation Interval=1HOUR
Output Interval=1HOUR
Run HTab= 0
Run UNet= 0
Run PostProcess= 0
Run WQNet= 0
UNET Theta= 1
UNET Theta Warmup= 1
UNET ZTol= 0.02
UNET ZSATol= 0.05
UNET MxIter= 20
UNET MaxInSteps= 0
UNET DtIC= 0
UNET DtMin= 0
UNET MaxCRTS= 20
UNET WFStab= 2
UNET SFStab= 1
UNET WFX= 1
UNET SFX= 1
UNET DSS MLevel= 4
UNET DZMax Abort= 100
UNET Convert EG Bridges= 0
UNET Use Existing IB Tables=-1
UNET Froude Reduction=False
UNET Froude Limit= 1
UNET Froude Power= 10
UNET Time Slicing=0,0, 5
UNET Junction Losses=0
Instantaneous Interval=1HOUR
Write IC File= 0
Write IC File at Sim End=0
Echo Input=False
Echo Parameters=False
Echo Output=False
Write Detailed= 0
WQ AD Non Conservative
WQ ULTIMATE=-1
WQ Max Comp Step=1HOUR
WQ Output Interval=15MIN
WQ Output Selected Increments= 0
WQ Output face flow=0
WQ Output face velocity=0
WQ Output face area=0
WQ Output face dispersion=0
WQ Output cell volume=0
WQ Output cell surface area=0
WQ Output cell continuity=0
WQ Output cumulative cell continuity=0
WQ Output face conc=0
WQ Output face dconc_dx=0
WQ Output face courant=0
WQ Output face peclet=0
WQ Output face adv mass=0
WQ Output face disp mass=0
WQ Output cell mass=0
WQ Output cell source sink temp=0
WQ Output cell source sink nsm=0
WQ Output MaxMinRange=-1
WQ Daily Max Min Mean=-1
WQ Daily Range=0
WQ Daily Time=0
WQ Create Restart=0
WQ Fixed Restart=0
WQ System Summary=0
WQ Use Fixed Temperature=0
Sorting and Armoring Iterations= 10
XS Update Threshold= 0.02
Hydraulics Update Threshold= 0.02
Energy Slope Method= 1
Volume Change Method= 0
XS Weighting Method= 0
Number of US Weighted Cross Sections= 1
Number of DS Weighted Cross Sections= 1
Upstream XS Weight=0.25
Main XS Weight=0.5
Downstream XS Weight=0.25
Number of DS XS's Weighted with US Boundary= 1
Upstream Boundary Weight= 1
Weight of XSs Associated with US Boundary= 0
Number of US XS's Weighted with DS Boundary= 1
Downstream Boundary Weight= 0.5
Weight of XSs Associated with DS Boundary= 0.5
Sediment Output Level= 4
Mass or Volume Output= 0
Output Increment Type= 1
Profile and TS Output Increment= 10
XS Output Flag= 0
XS Output Increment= 10
Disregard all LS=0
Disregard all Conn=0
Disregard all Breaches=0
Disregard all Pumps=0

--- Elm 01 27.f01 (steady flow) ---

Flow Title=Multiple
Number of Profiles=7
Profile Names=10-year,25-year,50-year,1pct_min,100-year,1pct_plu,500-year
River Rch & RM= Elm 01 27,Reach-1,18872
     205     282     345     263     421     580     634
River Rch & RM= Elm 01 27,Reach-1,17065
     303     425     527     405     648     892     996
River Rch & RM= Elm 01 27,Reach-1,14180
     415     590     737     570     913    1260    1420
River Rch & RM= Elm 01 27,Reach-1,8031
     639     925    1170     915    1470    2020    2340
River Rch & RM= Elm 01 27,Reach-1,3956
     673     974    1230     963    1540    2120    2460
River Rch & RM= Elm 01 27,Reach-1,1286
     725    1050    1330    1040    1670    2300    2670
Boundary for River Rch & Prof#=Elm 01 27,Reach-1,1
Up Type=0
Dn Type=3
Dn Slope=0.005
Boundary for River Rch & Prof#=Elm 01 27,Reach-1,2
Up Type=0
Dn Type=3
Dn Slope=0.005
Boundary for River Rch & Prof#=Elm 01 27,Reach-1,3
Up Type=0
Dn Type=3
Dn Slope=0.005
Boundary for River Rch & Prof#=Elm 01 27,Reach-1,4
Up Type=0
Dn Type=3
Dn Slope=0.005
Boundary for River Rch & Prof#=Elm 01 27,Reach-1,5
Up Type=0
Dn Type=3
Dn Slope=0.005
Boundary for River Rch & Prof#=Elm 01 27,Reach-1,6
Up Type=0
Dn Type=3
Dn Slope=0.005
Boundary for River Rch & Prof#=Elm 01 27,Reach-1,7
Up Type=0
Dn Type=3
Dn Slope=0.005

--- Elm 01 27.g01 (geometry) ---

Geom Title=Existing Conditions
Program Version=4.10

River Reach=Elm 01 27       ,Reach-1
Reach XY= 30
        1531155.        6817888.      1531699.48      6818385.57
      1531860.45      6819140.47      1532201.55      6819389.25
      1532105.69      6819727.25      1532365.33      6820298.17
      1532898.07      6820679.11      1533161.09      6820646.14
      1533560.85      6821185.96      1533846.66      6821140.98
      1535468.63      6822401.46      1535602.53      6822782.55
      1536415.15      6822798.69      1536162.48      6823094.04
      1536844.94       6823926.9      1538044.37      6824387.36
      1538298.81      6824045.82      1539210.89      6823639.96
      1539527.94      6823788.38      1539864.49      6823589.04
      1540123.29      6823738.08      1540389.91      6823638.18
      1540597.23      6823884.59      1540552.41      6824183.03
      1541139.78      6824287.48      1541408.44      6824095.39
      1541460.01      6824383.01       1541761.5      6824295.62
      1542252.72      6824932.18        1542705.        6824888.

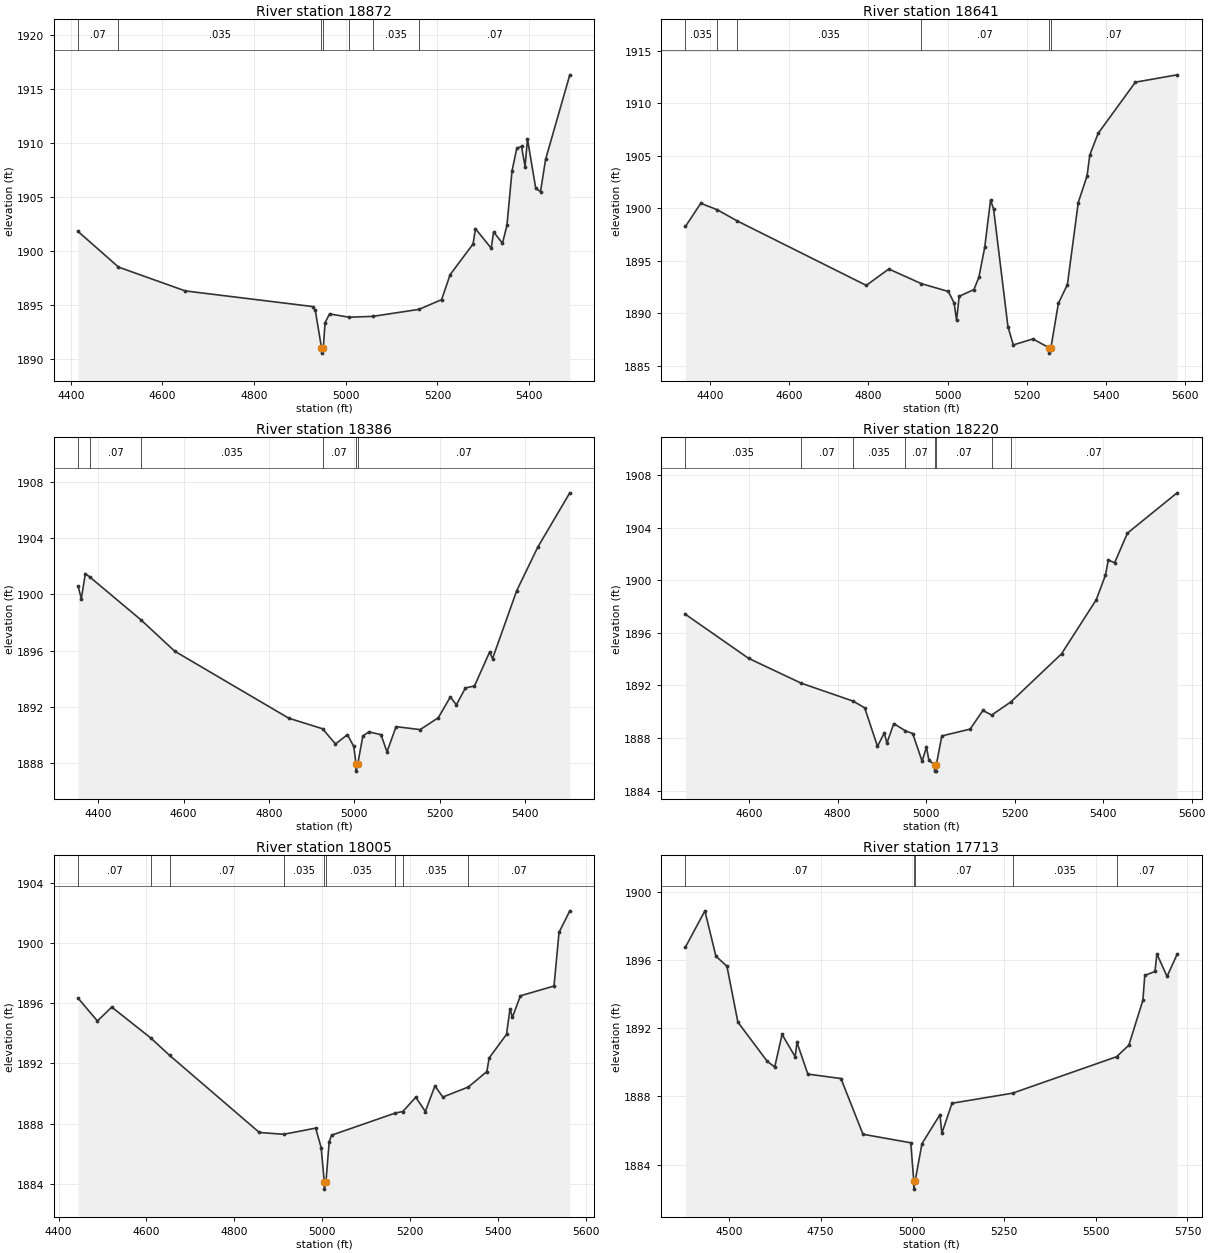
Type RM Length L Ch R = 1 ,18872   ,231,231,231
BEGIN DESCRIPTION:
Elm 01 27 18872.191
END DESCRIPTION:
XS GIS Cut Line= 3
      1530914.71      6818388.51      1531215.27      6817887.67
      1531345.23      6817416.36
#Sta/Elev= 30
  4415.9 1901.79    4504 1898.49  4649.7 1896.28  4927.6 1894.83  4933.5 1894.48
    4947 1891.01  4947.3 1890.51    4951 1891.01  4954.8 1893.33  4964.6 1894.15
  5007.2 1893.84  5059.1 1893.92  5159.9 1894.57  5209.1 1895.47  5227.9  1897.8
  5277.8 1900.63    5283 1902.05  5317.4 1900.24  5322.6 1901.75    5342  1900.7
  5351.8 1902.38  5362.7 1907.38  5373.1 1909.49  5383.5 1909.69  5391.3 1907.81
  5396.5 1910.38  5414.6 1905.79    5425 1905.49  5436.1 1908.48  5488.9 1916.32
#Mann= 7 ,-1 , 0
  4415.9     .07       0    4504    .035       0    4947    .035       0
    4951    .035       0  5007.2     .07       0  5059.1    .035       0
  5159.9     .07       0
Bank Sta=4947,4951
XS Rating Curve= 0 ,0
Exp/Cntr=0.3,0.1

Type RM Length L Ch R = 1 ,18641   ,255,255,255
BEGIN DESCRIPTION:
Elm 01 27 18641.15
END DESCRIPTION:
XS GIS Cut Line= 3
      1530942.49      6818510.04      1531303.58      6818110.76
       1531720.1      6817544.98
#Sta/Elev= 30
  4338.5 1898.25  4377.2 1900.46  4418.8 1899.84  4469.6 1898.77  4794.9 1892.64
  4851.7  1894.2  4933.7 1892.81    5002 1892.06  5016.6 1890.97  5022.8 1889.31
  5029.3  1891.6  5066.5 1892.24  5079.2 1893.42  5093.8 1896.26  5108.5 1900.76
  5116.2 1899.92  5152.4 1888.72  5165.9 1886.97  5215.5 1887.54  5256.9 1886.69
  5257.1 1886.19  5260.9 1886.69  5279.7 1890.93  5302.5 1892.71  5329.9 1900.53
  5352.1 1903.06  5359.1 1905.07    5380 1907.11  5474.1 1911.99  5579.4 1912.69
#Mann= 6 ,-1 , 0
  4338.5    .035       0  4418.8     .07       0  4469.6    .035       0
  4933.7     .07       0  5256.9     .07       0  5260.9     .07       0
Bank Sta=5256.9,5260.9
XS Rating Curve= 0 ,0
Exp/Cntr=0.3,0.1

Type RM Length L Ch R = 1 ,18386   ,166,166,166
BEGIN DESCRIPTION:
Elm 01 27 18385.51
END DESCRIPTION:
XS GIS Cut Line= 3
      1530970.23       6818544.8      1531511.91      6818204.51
      1531879.97      6817846.87
#Sta/Elev= 30
  4352.5 1900.57    4360 1899.69  4369.4 1901.47  4380.7 1901.21  4499.7 1898.19
    4579 1895.96  4846.4  1891.2  4925.6 1890.45    4956 1889.37    4984 1890.03
  4998.9 1889.19  5004.1 1887.94  5004.4 1887.44  5008.1 1887.94  5020.2 1889.94
  5034.4 1890.23  5062.7 1890.03  5076.8 1888.81    5098  1890.6  5154.5 1890.39
    5197 1891.23  5225.3 1892.71  5239.4 1892.15  5260.7 1893.35  5281.9 1893.49
  5317.2 1895.89  5324.3 1895.44  5380.9 1900.26  5430.3 1903.35  5505.4 1907.21
#Mann= 6 ,-1 , 0
  4352.5    .035       0  4380.7     .07       0  4499.7    .035       0
  4925.6     .07       0  5004.1     .07       0  5008.1     .07       0
Bank Sta=5004.1,5008.1
XS Rating Curve= 0 ,0
Exp/Cntr=0.3,0.1

Type RM Length L Ch R = 1 ,18220   ,215,215,215
BEGIN DESCRIPTION:
Elm 01 27 18220.47
END DESCRIPTION:
XS GIS Cut Line= 3
      1531168.18      6818596.86      1531640.38      6818312.15
      1532076.95      6817962.21
#Sta/Elev= 30
  4456.3 1897.42  4598.9 1894.07  4717.6 1892.18  4835.2 1890.81  4861.3  1890.3
  4890.2 1887.37  4905.7 1888.39  4911.5 1887.61    4927  1889.1  4952.8 1888.56
  4969.8 1888.34  4991.1 1886.23  5000.8 1887.31  5006.6 1886.29  5019.2 1885.98
  5019.4 1885.48  5022.9 1885.48  5023.2 1885.98  5035.6 1888.16  5099.6 1888.68
  5128.4  1890.1  5148.3 1889.75  5191.6 1890.75    5306 1894.41  5384.5 1898.53
  5405.3  1900.4  5411.7 1901.55  5426.1 1901.35  5454.9  1903.6  5567.2 1906.67
#Mann= 8 ,-1 , 0
  4456.3    .035       0  4717.6     .07       0  4835.2    .035       0
  4952.8     .07       0  5019.2     .07       0  5023.2     .07       0
  5148.3    .035       0  5191.6     .07       0
Bank Sta=5019.2,5023.2
XS Rating Curve= 0 ,0
Exp/Cntr=0.3,0.1

Type RM Length L Ch R = 1 ,18005   ,292,292,292
BEGIN DESCRIPTION:
Elm 01 27 18005.21
END DESCRIPTION:
XS GIS Cut Line= 3
      1531188.96      6818666.33       1531713.3      6818503.12
      1532237.59       6818280.9
#Sta/Elev= 30
  4444.5 1896.33  4488.4 1894.82    4521 1895.74  4609.4  1893.7  4652.9 1892.53
  4856.8 1887.42  4912.4  1887.3    4985 1887.71  4997.5  1886.4  5004.4 1884.16
  5004.6 1883.66  5008.4 1884.16  5015.7 1886.81  5021.1 1887.24  5166.2 1888.71
  5183.2 1888.81  5212.7 1889.76  5234.4 1888.81  5256.2 1890.51  5274.2 1889.77
  5332.4 1890.44  5374.3 1891.46  5379.7 1892.37  5419.1 1893.93  5427.1 1895.63
  5432.5 1895.06  5450.7 1896.49  5527.2 1897.14  5538.6  1900.7  5563.1 1902.13
#Mann= 9 ,-1 , 0
  4444.5     .07       0  4609.4    .035       0  4652.9     .07       0
  4912.4    .035       0  5004.4    .035       0  5008.4    .035       0
  5166.2     .07       0  5183.2    .035       0  5332.4     .07       0
Bank Sta=5004.4,5008.4
XS Rating Curve= 0 ,0
Exp/Cntr=0.3,0.1

Type RM Length L Ch R = 1 ,17713   ,255,255,255
BEGIN DESCRIPTION:
Elm 01 27 17713.47
END DESCRIPTION:
XS GIS Cut Line= 3
      1531102.15      6818742.71      1531734.13      6818701.04
      1532410.59      6818496.37
#Sta/Elev= 30
  4381.7 1896.76  4434.7 1898.89  4464.7 1896.23  4494.8 1895.64  4524.6 1892.36
    4605 1890.05  4625.1 1889.73  4645.1 1891.64  4680.7 1890.33  4685.7 1891.17
  4715.3 1889.31  4805.5 1889.05  4865.6 1885.78  4995.9 1885.28  5003.9 1883.06
  5004.2 1882.56  5007.9 1883.06  5026.4 1885.23  5075.4 1886.93  5080.6 1885.84
  5108.3  1887.6  5273.2 1888.19  5556.9 1890.33  5590.3 1891.01  5628.5 1893.64
  5633.7  1895.1  5661.4 1895.33  5666.7 1896.36  5694.4 1895.04  5721.8 1896.34
#Mann= 5 ,-1 , 0
  4381.7     .07       0  5003.9     .07       0  5007.9     .07       0
  5273.2    .035       0  5556.9     .07       0
Bank Sta=5003.9,5007.9
XS Rating Curve= 0 ,0
Exp/Cntr=0.3,0.1

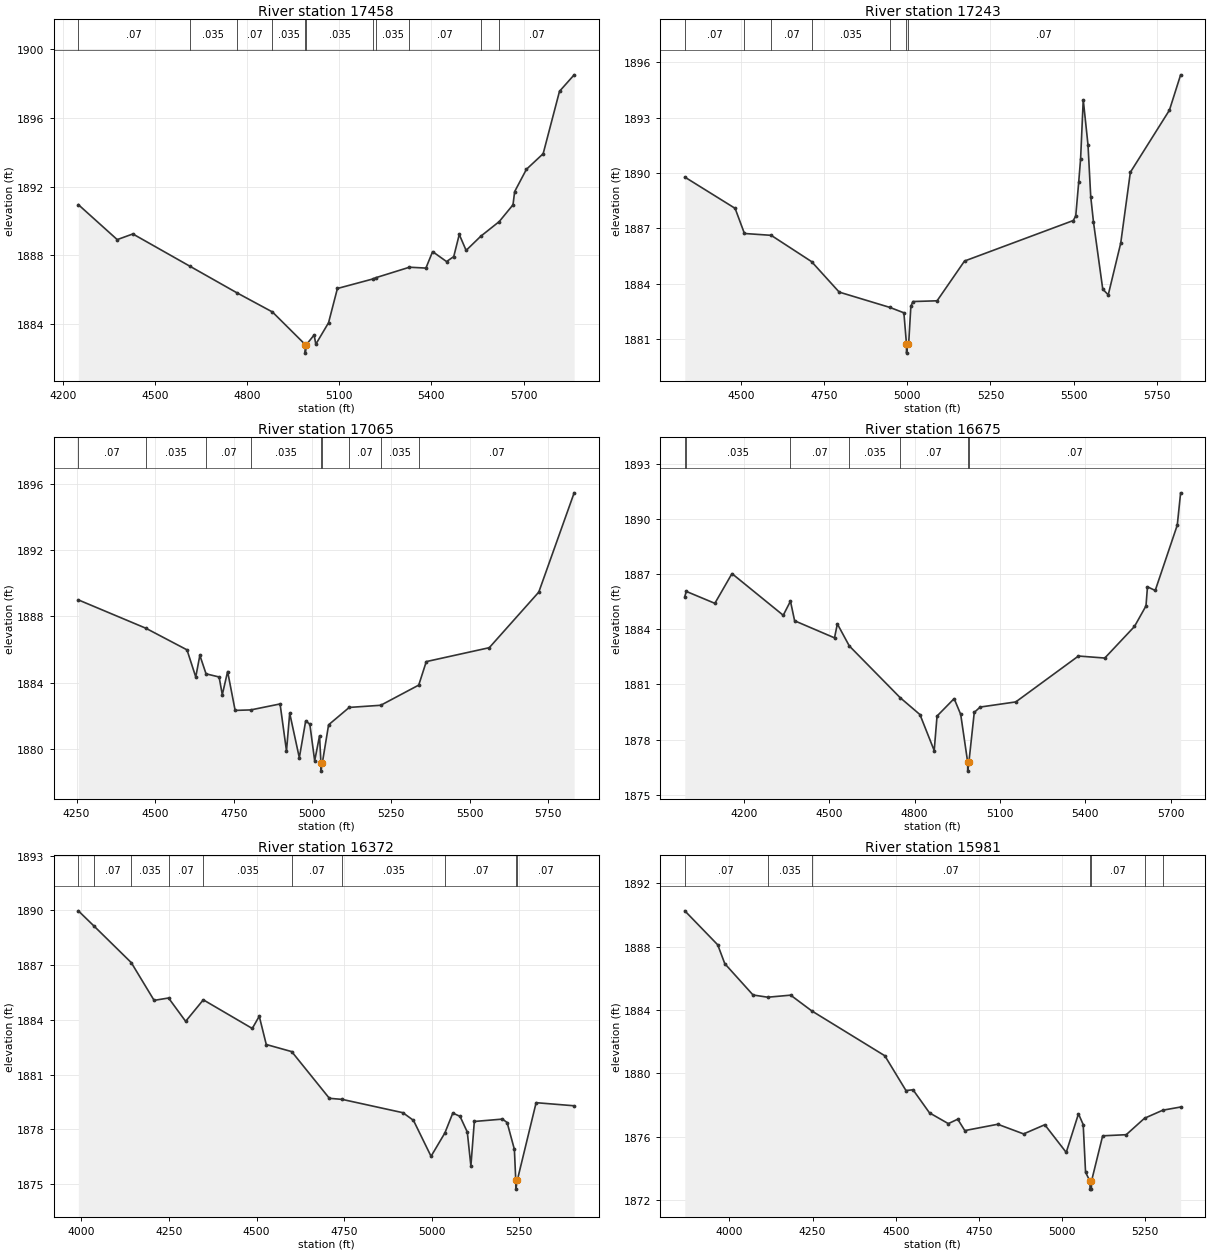
Type RM Length L Ch R = 1 ,17458   ,215,215,215
BEGIN DESCRIPTION:
Elm 01 27 17457.9
END DESCRIPTION:
XS GIS Cut Line= 3
      1531029.23      6818992.71      1531786.21       6818905.9
      1532567.48      6818565.62
#Sta/Elev= 30
  4250.8 1890.95  4377.4 1888.91  4428.3 1889.24  4612.8 1887.37  4766.8 1885.81
  4882.7 1884.69  4989.4 1882.79  4989.6 1882.29  4993.4 1882.79  5018.4 1883.35
  5023.9 1882.81  5065.3 1884.06  5094.2 1886.06  5208.6 1886.61  5219.4 1886.69
  5328.7  1887.3  5382.3 1887.25  5404.1 1888.21  5449.5 1887.63  5472.9 1887.92
  5490.9 1889.21  5513.2 1888.28  5561.1 1889.11  5620.9 1889.96  5665.8 1890.94
  5671.2 1891.71  5709.5 1893.01    5764 1893.92  5817.2 1897.56  5864.9 1898.52
#Mann= 11 ,-1 , 0
  4250.8     .07       0  4612.8    .035       0  4766.8     .07       0
  4882.7    .035       0  4989.4    .035       0  4993.4    .035       0
  5208.6     .07       0  5219.4    .035       0  5328.7     .07       0
  5561.1    .035       0  5620.9     .07       0
Bank Sta=4989.4,4993.4
XS Rating Curve= 0 ,0
Exp/Cntr=0.3,0.1

Type RM Length L Ch R = 1 ,17243   ,178,178,178
BEGIN DESCRIPTION:
Elm 01 27 17243.36
END DESCRIPTION:
XS GIS Cut Line= 3
      1531195.97       6819180.2      1531859.13      6819069.09
      1532584.86      6818694.08
#Sta/Elev= 30
  4331.8 1889.78  4482.9 1888.09  4510.9 1886.73  4591.3 1886.63  4712.5 1885.21
  4795.6 1883.56  4948.1 1882.73  4989.9 1882.44  4997.6 1880.76  4997.8 1880.26
  5001.6 1880.76  5004.2 1880.76  5010.8 1882.79    5017 1883.05  5089.6 1883.09
    5172 1885.24  5498.6 1887.43  5506.1 1887.68  5515.1 1889.53  5520.7 1890.78
  5528.6 1893.96  5542.9 1891.52  5551.1 1888.72  5559.4 1887.34  5587.2 1883.72
  5603.7 1883.41  5641.2 1886.21  5670.1 1890.04  5787.5  1893.4  5821.1 1895.31
#Mann= 7 ,-1 , 0
  4331.8     .07       0  4510.9    .035       0  4591.3     .07       0
  4712.5    .035       0  4948.1     .07       0  4997.6     .07       0
  5001.6     .07       0
Bank Sta=4997.6,5001.6
XS Rating Curve= 0 ,0
Exp/Cntr=0.3,0.1

Type RM Length L Ch R = 1 ,17065   ,390,390,390
BEGIN DESCRIPTION:
Elm 01 27 17065.37
END DESCRIPTION:
XS GIS Cut Line= 3
      1531206.36      6819367.71       1531925.1      6819221.87
      1532675.08      6818836.47
#Sta/Elev= 30
  4255.8    1889  4470.1 1887.29  4601.3 1885.98  4629.2 1884.34  4642.2 1885.65
  4661.9 1884.53  4703.4 1884.34  4713.6 1883.27  4730.5 1884.67  4754.4 1882.32
  4804.3 1882.35  4897.3 1882.71  4917.7 1879.87  4927.9 1882.15  4958.5 1879.46
  4978.7 1881.68  4991.9 1881.49  5007.3 1879.27  5022.8 1880.79  5027.2 1879.15
  5027.5 1878.65  5031.7 1879.15  5051.6 1881.45  5117.2  1882.5  5217.4 1882.63
  5338.2 1883.85  5362.2 1885.27  5562.5 1886.11  5719.9 1889.47  5832.4 1895.47
#Mann= 9 ,-1 , 0
  4255.8     .07       0  4470.1    .035       0  4661.9     .07       0
  4804.3    .035       0  5027.2    .035       0  5031.7    .035       0
  5117.2     .07       0  5217.4    .035       0  5338.2     .07       0
Bank Sta=5027.2,5031.7
XS Rating Curve= 0 ,0
Exp/Cntr=0.3,0.1

Type RM Length L Ch R = 1 ,16675   ,303,303,303
BEGIN DESCRIPTION:
Elm 01 27 16675.49
END DESCRIPTION:
XS GIS Cut Line= 3
      1531199.44      6819510.07      1532199.41      6819451.04
      1532910.58      6819239.42
#Sta/Elev= 30
  3991.9 1885.79  3997.2 1886.07  4097.6 1885.42  4157.8 1887.04  4338.1 1884.77
  4363.5 1885.54  4378.1 1884.47  4518.4 1883.54  4528.4  1884.3  4570.4  1883.1
  4749.4 1880.28  4818.9 1879.36    4869  1877.4    4879 1879.28  4939.1 1880.23
  4962.2 1879.37  4986.6 1876.78  4986.9 1876.28  4991.1 1876.78  5009.9 1879.48
  5030.7 1879.77  5155.9 1880.05  5376.3 1882.55  5468.9 1882.44  5573.3 1884.16
  5613.8 1885.28    5619 1886.32  5646.3 1886.12  5723.8 1889.68  5735.6 1891.44
#Mann= 7 ,-1 , 0
  3991.9     .07       0  3997.2    .035       0  4363.5     .07       0
  4570.4    .035       0  4749.4     .07       0  4986.6     .07       0
  4991.1     .07       0
Bank Sta=4986.6,4991.1
XS Rating Curve= 0 ,0
Exp/Cntr=0.3,0.1

Type RM Length L Ch R = 1 ,16372   ,391,391,391
BEGIN DESCRIPTION:
Elm 01 27 16372.03
END DESCRIPTION:
XS GIS Cut Line= 3
      1531098.76      6819739.23      1532098.71      6819697.57
        1532500.      6819591.06
#Sta/Elev= 30
  3991.1 1889.98  4035.1 1889.16  4142.3 1887.14  4207.5 1885.07  4248.8  1885.2
  4297.6 1883.92    4348  1885.1  4487.8 1883.53  4507.8  1884.2  4527.8 1882.65
  4600.5 1882.26    4708  1879.7  4744.8 1879.64  4918.1 1878.91  4948.2 1878.49
  4998.4 1876.52  5037.9  1877.8  5060.5 1878.89  5081.2 1878.71  5101.9 1877.85
  5112.2 1875.99    5122 1878.43  5202.4 1878.56  5215.7 1878.37  5236.4  1876.9
  5240.3 1875.22  5240.6 1874.72  5244.9 1875.22  5298.5 1879.46  5407.1 1879.29
#Mann= 10 ,-1 , 0
  3991.1    .035       0  4035.1     .07       0  4142.3    .035       0
  4248.8     .07       0    4348    .035       0  4600.5     .07       0
  4744.8    .035       0  5037.9     .07       0  5240.3    .035       0
  5244.9     .07       0
Bank Sta=5240.3,5244.9
XS Rating Curve= 0 ,0
Exp/Cntr=0.3,0.1

Type RM Length L Ch R = 1 ,15981   ,291,291,291
BEGIN DESCRIPTION:
Elm 01 27 15981.194
END DESCRIPTION:
XS GIS Cut Line= 3
        1531455.        6820838.      1532260.85      6820040.29
      1532565.29      6819855.39
#Sta/Elev= 30
  3866.1 1890.27  3965.1 1888.12  3986.3 1886.93  4071.2 1884.95  4115.4 1884.81
  4184.3 1884.94  4247.3 1883.95  4467.2 1881.11  4530.8 1878.91    4552 1878.96
  4601.5  1877.5  4658.1 1876.82  4686.3  1877.1  4707.6 1876.38  4806.6 1876.78
  4884.3 1876.17    4948 1876.75  5012.4    1875  5049.2 1877.44  5063.4 1876.76
  5070.5 1873.75  5083.7 1873.18  5084.1 1872.68    5088 1872.68  5088.3 1873.18
  5121.9 1876.05  5192.7 1876.12  5247.7 1877.16  5302.8 1877.67  5356.2 1877.87
#Mann= 7 ,-1 , 0
  3866.1     .07       0  4115.4    .035       0  4247.3     .07       0
  5083.7     .07       0  5088.3     .07       0  5247.7    .035       0
  5302.8     .07       0
Bank Sta=5083.7,5088.3
XS Rating Curve= 0 ,0
Exp/Cntr=0.3,0.1

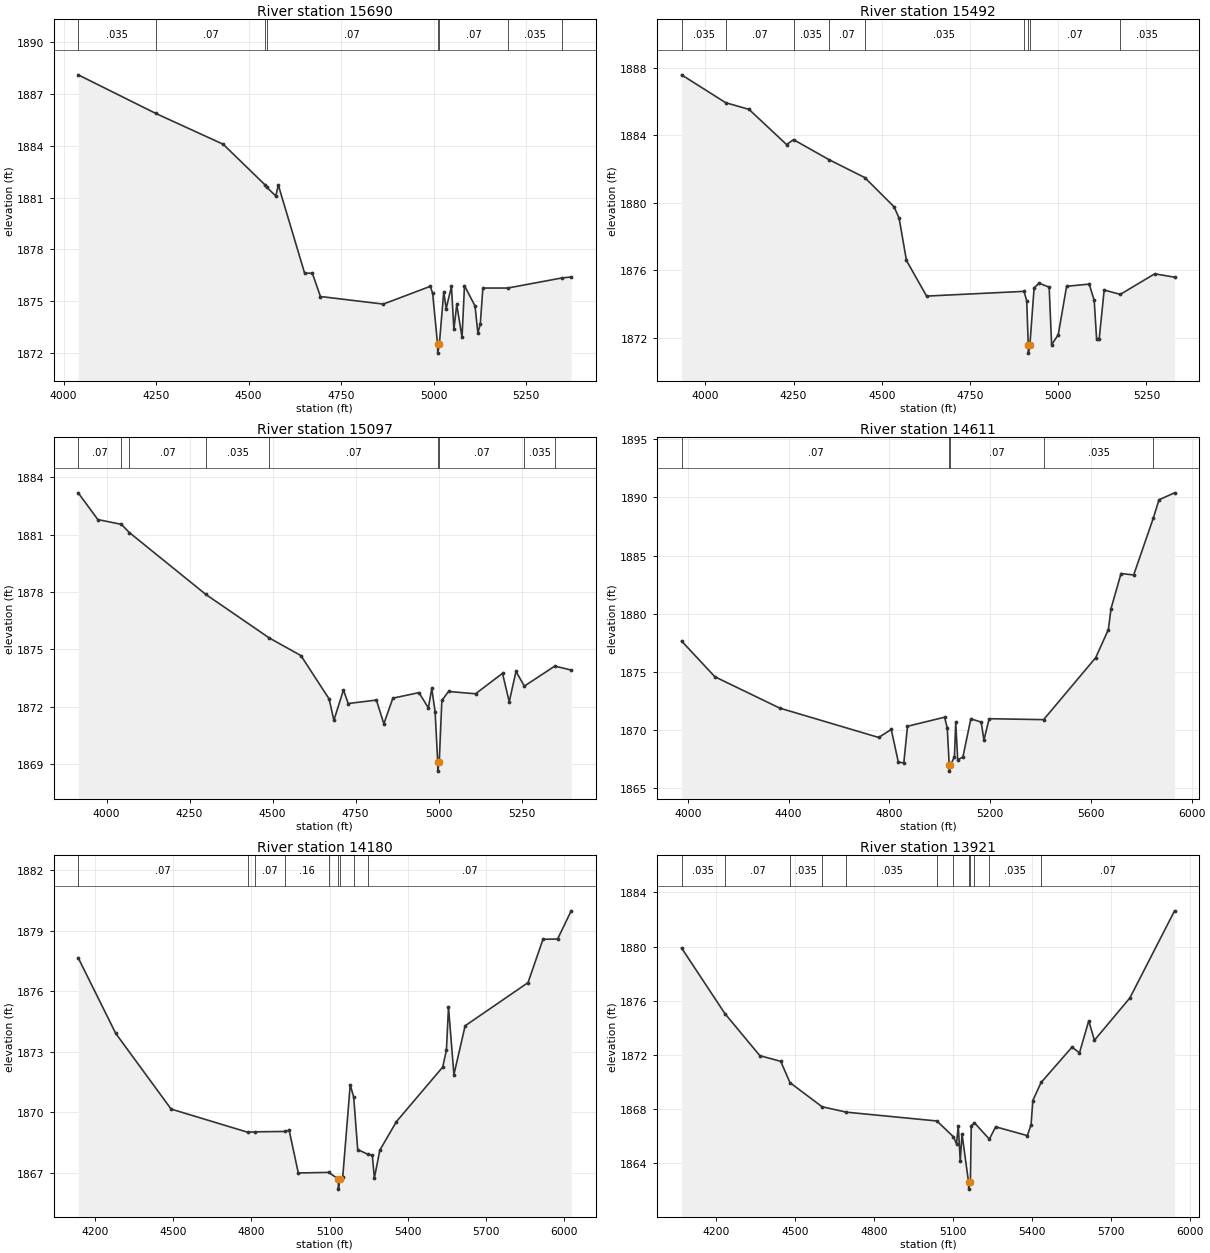
Type RM Length L Ch R = 1 ,15690   ,198,198,198
BEGIN DESCRIPTION:
Elm 01 27 15689.66
END DESCRIPTION:
XS GIS Cut Line= 3
      1531640.35      6820926.76       1532362.6      6820294.79
      1532647.44      6820054.44
#Sta/Elev= 30
  4039.7 1888.11  4249.8 1885.87  4431.5 1884.09  4545.5 1881.72  4548.9 1881.61
  4573.8 1881.09  4580.5 1881.73  4651.7 1876.62  4672.5 1876.62  4694.4 1875.27
  4864.3 1874.83  4991.4 1875.86  4997.7 1875.45    5011 1872.49  5011.4 1871.99
  5015.7 1872.49  5027.7 1875.55  5034.2 1874.57  5048.5 1875.85  5055.1 1873.36
  5062.8 1874.81  5077.1  1872.9  5083.7  1875.9  5112.2 1874.72    5120 1873.14
  5126.5  1873.7  5133.4 1875.76  5200.5 1875.76  5348.4 1876.35  5372.1  1876.4
#Mann= 8 ,-1 , 0
  4039.7    .035       0  4249.8     .07       0  4545.5    .035       0
  4548.9     .07       0    5011     .07       0  5015.7     .07       0
  5200.5    .035       0  5348.4     .07       0
Bank Sta=5011,5015.7
XS Rating Curve= 0 ,0
Exp/Cntr=0.3,0.1

Type RM Length L Ch R = 1 ,15492   ,395,395,395
BEGIN DESCRIPTION:
Elm 01 27 15491.927
END DESCRIPTION:
XS GIS Cut Line= 4
      1531705.01      6821087.99      1532509.15      6820385.92
      1532683.62      6820223.46      1532725.49      6820142.44
#Sta/Elev= 30
  3932.5 1887.58  4057.5 1885.93  4123.8 1885.53  4230.1 1883.45  4249.8 1883.74
  4350.7 1882.55  4451.9 1881.49  4534.8 1879.76    4549 1879.09  4569.9 1876.58
  4626.9 1874.47    4903 1874.75  4910.7 1874.19    4915 1871.59  4915.3 1871.09
  4919.7 1871.59  4931.6 1874.96  4945.8 1875.23  4974.3    1875  4981.2 1871.59
    5000 1872.18  5023.7 1875.05  5087.7 1875.18  5101.9 1874.22  5108.7 1871.94
  5116.1 1871.94  5130.2 1874.83  5175.8 1874.57  5273.4 1875.79  5329.6 1875.59
#Mann= 9 ,-1 , 0
  3932.5    .035       0  4057.5     .07       0  4249.8    .035       0
  4350.7     .07       0  4451.9    .035       0    4903     .07       0
    4915     .07       0  4919.7     .07       0  5175.8    .035       0
Bank Sta=4915,4919.7
XS Rating Curve= 0 ,0
Exp/Cntr=0.3,0.1

Type RM Length L Ch R = 1 ,15097   ,486,486,486
BEGIN DESCRIPTION:
Elm 01 27 15001.15
END DESCRIPTION:
XS GIS Cut Line= 3
      1532004.94      6821280.92      1532818.46      6820631.93
      1532894.22      6820194.11
#Sta/Elev= 30
  3914.5 1883.19  3973.7 1881.79  4044.7 1881.54  4068.6 1881.11  4299.1 1877.87
  4490.2 1875.59  4585.4 1874.67  4670.3  1872.4  4684.7 1871.28  4713.5 1872.87
  4727.9 1872.16  4812.8 1872.34  4835.2  1871.1  4862.4 1872.44  4940.9 1872.73
  4969.3 1871.93  4979.5 1872.95  4989.6 1871.73  4997.4 1869.12  4997.7 1868.62
  5002.1 1869.12  5009.9 1872.32  5030.2 1872.79  5111.4 1872.67  5192.6 1873.74
  5212.9 1872.25  5233.2 1873.84  5258.4 1873.07  5350.2 1874.12  5399.5 1873.91
#Mann= 9 ,-1 , 0
  3914.5     .07       0  4044.7    .035       0  4068.6     .07       0
  4299.1    .035       0  4490.2     .07       0  4997.4     .07       0
  5002.1     .07       0  5258.4    .035       0  5350.2     .07       0
Bank Sta=4997.4,5002.1
XS Rating Curve= 0 ,0
Exp/Cntr=0.3,0.1

Type RM Length L Ch R = 1 ,14611   ,431,431,431
BEGIN DESCRIPTION:
Elm 01 27 14611.03
END DESCRIPTION:
XS GIS Cut Line= 4
      1532571.93      6821491.06      1533191.67      6820681.54
      1533334.59      6820186.22       1533373.9      6819766.49
#Sta/Elev= 30
  3975.5 1877.66  4107.8 1874.59  4365.3  1871.9  4757.9 1869.38  4807.8 1870.07
  4835.7 1867.28  4857.6 1867.19  4872.2 1870.34  5019.5 1871.12  5030.1 1870.18
  5037.9 1866.99  5038.3 1866.49  5042.7 1866.99  5058.5 1867.72  5063.7 1870.68
  5071.5 1867.45  5092.2 1867.71  5123.6 1870.98  5164.7  1870.7  5175.6 1869.16
  5196.4 1870.99  5412.5 1870.91  5619.2 1876.23  5669.4 1878.64  5680.1 1880.45
  5719.7 1883.45  5769.9 1883.33  5847.8 1888.21  5870.3 1889.78  5932.1 1890.38
#Mann= 5 ,-1 , 0
  3975.5     .07       0  5037.9     .07       0  5042.7     .07       0
  5412.5    .035       0  5847.8     .07       0
Bank Sta=5037.9,5042.7
XS Rating Curve= 0 ,0
Exp/Cntr=0.3,0.1

Type RM Length L Ch R = 1 ,14180   ,259,259,259
BEGIN DESCRIPTION:
Elm 01 27 14180.06
END DESCRIPTION:
XS GIS Cut Line= 3
      1532724.55      6821581.28      1533353.05       6820987.5
      1534148.19      6820338.19
#Sta/Elev= 30
  4135.9 1877.65    4280  1873.9  4492.4 1870.15  4786.4    1869  4812.5 1869.02
  4930.2 1869.04  4945.1  1869.1  4980.3 1866.98  5096.9 1867.01  5133.8 1866.68
  5134.2 1866.18  5138.9 1866.68  5150.7 1866.77  5179.4 1871.35  5192.7 1870.75
  5208.2 1868.14  5246.7 1867.91  5264.2 1867.86  5272.1 1866.73  5292.9 1868.11
  5356.8 1869.53  5534.1 1872.23  5548.5 1873.07  5556.4 1875.21  5577.2 1871.86
  5620.3 1874.28  5861.5 1876.42  5918.9 1878.57  5974.9 1878.58  6027.1 1879.98
#Mann= 9 ,-1 , 0
  4135.9     .07       0  4786.4    .035       0  4812.5     .07       0
  4930.2     .16       0  5096.9     .07       0  5133.8     .07       0
  5138.9     .07       0  5192.7     .16       0  5246.7     .07       0
Bank Sta=5133.8,5138.9
XS Rating Curve= 0 ,0
Exp/Cntr=0.3,0.1

Type RM Length L Ch R = 1 ,13921   ,508,508,508
BEGIN DESCRIPTION:
Elm 01 27 13921.17
END DESCRIPTION:
XS GIS Cut Line= 3
      1532748.88        6821675.      1533516.25      6821154.16
      1534220.14      6820523.09
#Sta/Elev= 30
  4069.2  1879.9  4234.1 1875.05  4366.7 1871.95    4446 1871.53  4481.1 1869.96
  4603.1 1868.18  4695.5 1867.78  5039.3 1867.13  5102.1 1865.96  5113.7 1865.44
  5120.4 1866.78  5127.9 1864.14  5134.6 1866.18  5159.6  1862.6  5160.1  1862.1
  5166.4  1862.6  5169.7 1866.76  5181.6    1867  5238.5 1865.79  5262.4  1866.7
  5382.8 1866.05    5397 1866.86  5403.7 1868.64    5435 1869.97  5552.5 1872.58
  5580.9 1872.16    5616 1874.52  5637.7 1873.09  5772.3 1876.21    5942 1882.64
#Mann= 12 ,-1 , 0
  4069.2    .035       0  4234.1     .07       0  4481.1    .035       0
  4603.1     .07       0  4695.5    .035       0  5039.3     .07       0
  5102.1    .035       0  5159.6    .035       0  5166.4    .035       0
  5181.6     .16       0  5238.5    .035       0    5435     .07       0
Bank Sta=5159.6,5166.4
XS Rating Curve= 0 ,0
Exp/Cntr=0.3,0.1

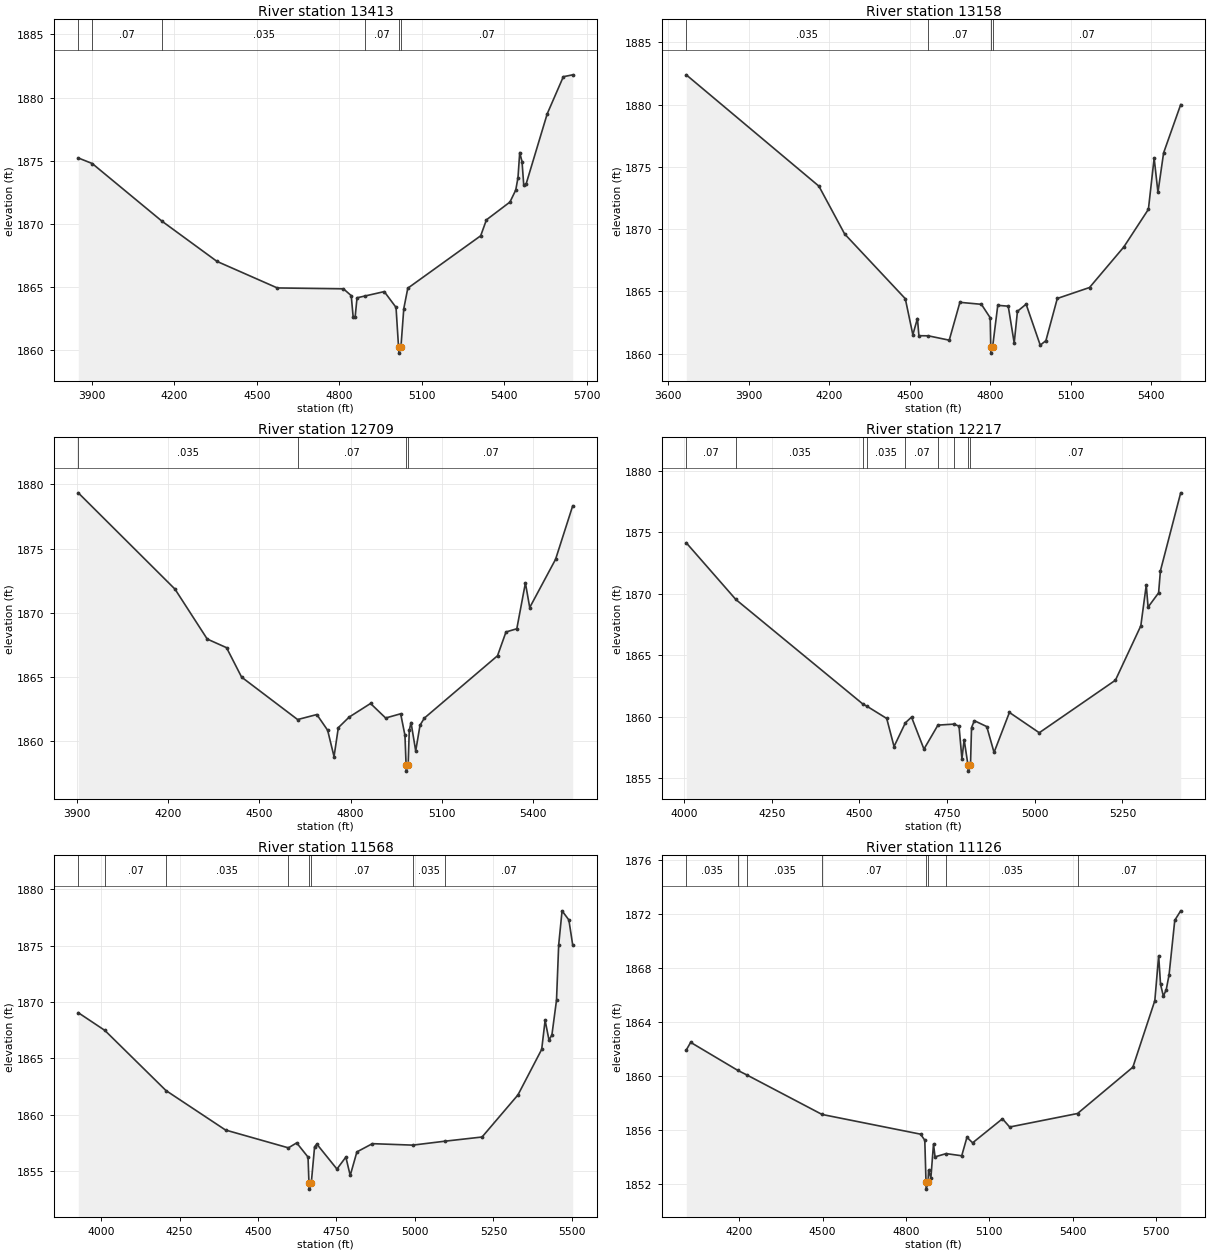
Type RM Length L Ch R = 1 ,13413   ,255,255,255
BEGIN DESCRIPTION:
Elm 01 27 13413.29
END DESCRIPTION:
XS GIS Cut Line= 3
       1533133.4      6822089.96      1533918.16      6821270.48
      1534451.42      6820875.73
#Sta/Elev= 30
    3851 1875.22  3901.7 1874.78  4155.7 1870.21  4355.6 1867.03  4574.8 1864.93
  4815.4 1864.86  4843.7 1864.32  4850.6 1862.65  4857.9 1862.63  4864.8 1864.15
  4895.2  1864.3  4963.8 1864.64  5006.6 1863.39  5015.7 1860.27  5017.2 1859.77
  5024.5 1860.27  5034.8 1863.29  5049.4 1864.91  5314.5 1869.06  5335.3 1870.32
  5420.9 1871.73    5442 1872.68  5450.1 1873.66  5456.4 1875.65  5464.8 1874.93
    5471 1873.09  5479.4 1873.14  5556.5 1878.72    5615 1881.65  5649.1  1881.8
#Mann= 6 ,-1 , 0
    3851    .035       0  3901.7     .07       0  4155.7    .035       0
  4895.2     .07       0  5015.7     .07       0  5024.5     .07       0
Bank Sta=5015.7,5024.5
XS Rating Curve= 0 ,0
Exp/Cntr=0.3,0.1

Type RM Length L Ch R = 1 ,13158   ,449,449,449
BEGIN DESCRIPTION:
Elm 01 27 13157.888
END DESCRIPTION:
XS GIS Cut Line= 3
      1533554.99      6822588.03      1534134.94      6821388.14
      1534504.96      6821038.03
#Sta/Elev= 30
  3667.3  1882.4  4161.5 1873.46  4257.4 1869.62  4483.4 1864.42  4511.5 1861.53
  4528.6 1862.83  4534.1 1861.45    4569 1861.44  4647.1 1861.09  4686.8 1864.13
  4766.9 1863.97  4799.7 1862.89  4801.8 1860.55  4802.3 1860.05  4808.7 1860.55
  4827.9 1863.89  4866.9 1863.82  4889.1 1860.86  4901.2 1863.41  4933.5 1863.98
  4986.1 1860.69  5007.2 1861.05  5049.7 1864.44  5169.8 1865.32  5297.3 1868.57
  5389.1  1871.6  5410.5 1875.71  5424.7 1872.96  5445.7 1876.13  5509.4 1880.01
#Mann= 4 ,-1 , 0
  3667.3    .035       0    4569     .07       0  4801.8     .07       0
  4808.7     .07       0
Bank Sta=4801.8,4808.7
XS Rating Curve= 0 ,0
Exp/Cntr=0.3,0.1

Type RM Length L Ch R = 1 ,12709   ,492,492,492
BEGIN DESCRIPTION:
Elm 01 27 12708.527
END DESCRIPTION:
XS GIS Cut Line= 3
      1533705.03      6822437.97      1534468.21      6821651.63
      1534855.01      6821287.99
#Sta/Elev= 30
  3904.2 1879.33  4222.5 1871.84  4328.5 1867.96    4392 1867.29  4441.6    1865
  4625.9  1861.7  4689.1 1862.09  4724.6 1860.87  4745.7 1858.82  4759.8 1861.07
  4795.3 1861.89  4865.8 1862.95  4915.5 1861.82  4964.9 1862.15    4979 1860.47
  4982.7 1858.19  4983.2 1857.69  4989.6 1858.19  4993.2 1860.86    4999 1861.47
  5014.4 1859.26  5028.6 1861.26  5042.7 1861.81  5283.5 1866.66  5311.4 1868.51
    5347 1868.76  5375.3 1872.32  5389.5 1870.41  5474.5 1874.16  5530.9 1878.32
#Mann= 4 ,-1 , 0
  3904.2    .035       0  4625.9     .07       0  4982.7     .07       0
  4989.6     .07       0
Bank Sta=4982.7,4989.6
XS Rating Curve= 0 ,0
Exp/Cntr=0.3,0.1

Type RM Length L Ch R = 1 ,12217   ,649,649,649
BEGIN DESCRIPTION:
Elm 01 27 12217.453
END DESCRIPTION:
XS GIS Cut Line= 3
      1534054.98      6822538.02      1534848.96       6821940.5
      1534954.99      6821538.03
#Sta/Elev= 30
  4006.3 1874.15  4147.7 1869.54  4510.5 1861.03  4521.8 1860.86  4577.9 1859.87
  4598.8 1857.59  4631.2 1859.52  4648.7 1859.98  4684.1 1857.38    4724 1859.33
  4769.2 1859.41  4784.1 1859.25  4792.4 1856.59  4798.7 1858.15  4809.6 1856.09
  4810.1 1855.59  4816.8 1856.09  4819.8 1859.13  4827.8 1859.69  4863.2 1859.21
    4884 1857.11  4927.8 1860.36  5012.9 1858.71  5230.1 1862.98  5302.5  1867.4
    5318 1870.71  5323.2 1868.92  5353.2 1870.08  5358.4 1871.87  5416.2 1878.21
#Mann= 9 ,-1 , 0
  4006.3     .07       0  4147.7    .035       0  4510.5     .07       0
  4521.8    .035       0  4631.2     .07       0    4724    .035       0
  4769.2     .07       0  4809.6     .07       0  4816.8     .07       0
Bank Sta=4809.6,4816.8
XS Rating Curve= 0 ,0
Exp/Cntr=0.3,0.1

Type RM Length L Ch R = 1 ,11568   ,442,442,442
BEGIN DESCRIPTION:
Elm 01 27 11567.71
END DESCRIPTION:
XS GIS Cut Line= 3
      1534644.73      6823140.27      1535346.11      6822338.19
      1535540.26      6821866.69
#Sta/Elev= 30
  3927.3 1869.05    4012 1867.48  4206.7 1862.15  4396.5 1858.65  4596.8 1857.07
  4623.3 1857.51  4659.4 1856.25  4662.4 1853.91  4662.9 1853.41  4669.6 1853.91
  4680.3 1857.17  4687.5  1857.4  4751.5 1855.19  4779.9 1856.25  4793.8 1854.62
  4815.1 1856.71  4864.4 1857.44  4993.1 1857.31  5095.8 1857.66  5213.9 1858.03
  5328.2 1861.76  5403.9  1865.8  5414.8 1868.37  5427.1 1866.63  5436.4 1867.07
  5451.1 1870.16    5458 1875.05  5468.8 1878.08  5490.5 1877.27  5502.7 1875.05
#Mann= 8 ,-1 , 0
  3927.3    .035       0    4012     .07       0  4206.7    .035       0
  4596.8     .07       0  4662.4    .035       0  4669.6     .07       0
  4993.1    .035       0  5095.8     .07       0
Bank Sta=4662.4,4669.6
XS Rating Curve= 0 ,0
Exp/Cntr=0.3,0.1

Type RM Length L Ch R = 1 ,11126   ,214,214,214
BEGIN DESCRIPTION:
Elm 01 27 11125.64
END DESCRIPTION:
XS GIS Cut Line= 3
      1535108.72      6823592.49        1535508.      6822689.75
      1535677.27      6821917.18
#Sta/Elev= 30
  4009.8 1861.95  4025.6 1862.52  4195.4 1860.44  4228.3  1860.1  4498.1 1857.18
  4852.4 1855.72  4867.6 1855.27    4872 1852.15  4872.5 1851.65  4879.3 1852.15
  4881.1 1853.04  4889.5 1852.49  4898.9 1854.99  4904.4 1854.04  4944.4 1854.28
  5000.4 1854.12  5019.2 1855.49  5039.6 1855.08  5146.8 1856.86  5172.7 1856.25
  5416.8 1857.25  5615.8 1860.68  5694.8 1865.61  5708.6 1868.94  5715.3 1866.82
  5725.5 1865.94  5735.8 1866.42    5746 1867.52  5766.5 1871.56  5787.8 1872.26
#Mann= 8 ,-1 , 0
  4009.8    .035       0  4195.4     .07       0  4228.3    .035       0
  4498.1     .07       0    4872    .035       0  4879.3     .07       0
  4944.4    .035       0  5416.8     .07       0
Bank Sta=4872,4879.3
XS Rating Curve= 0 ,0
Exp/Cntr=0.3,0.1