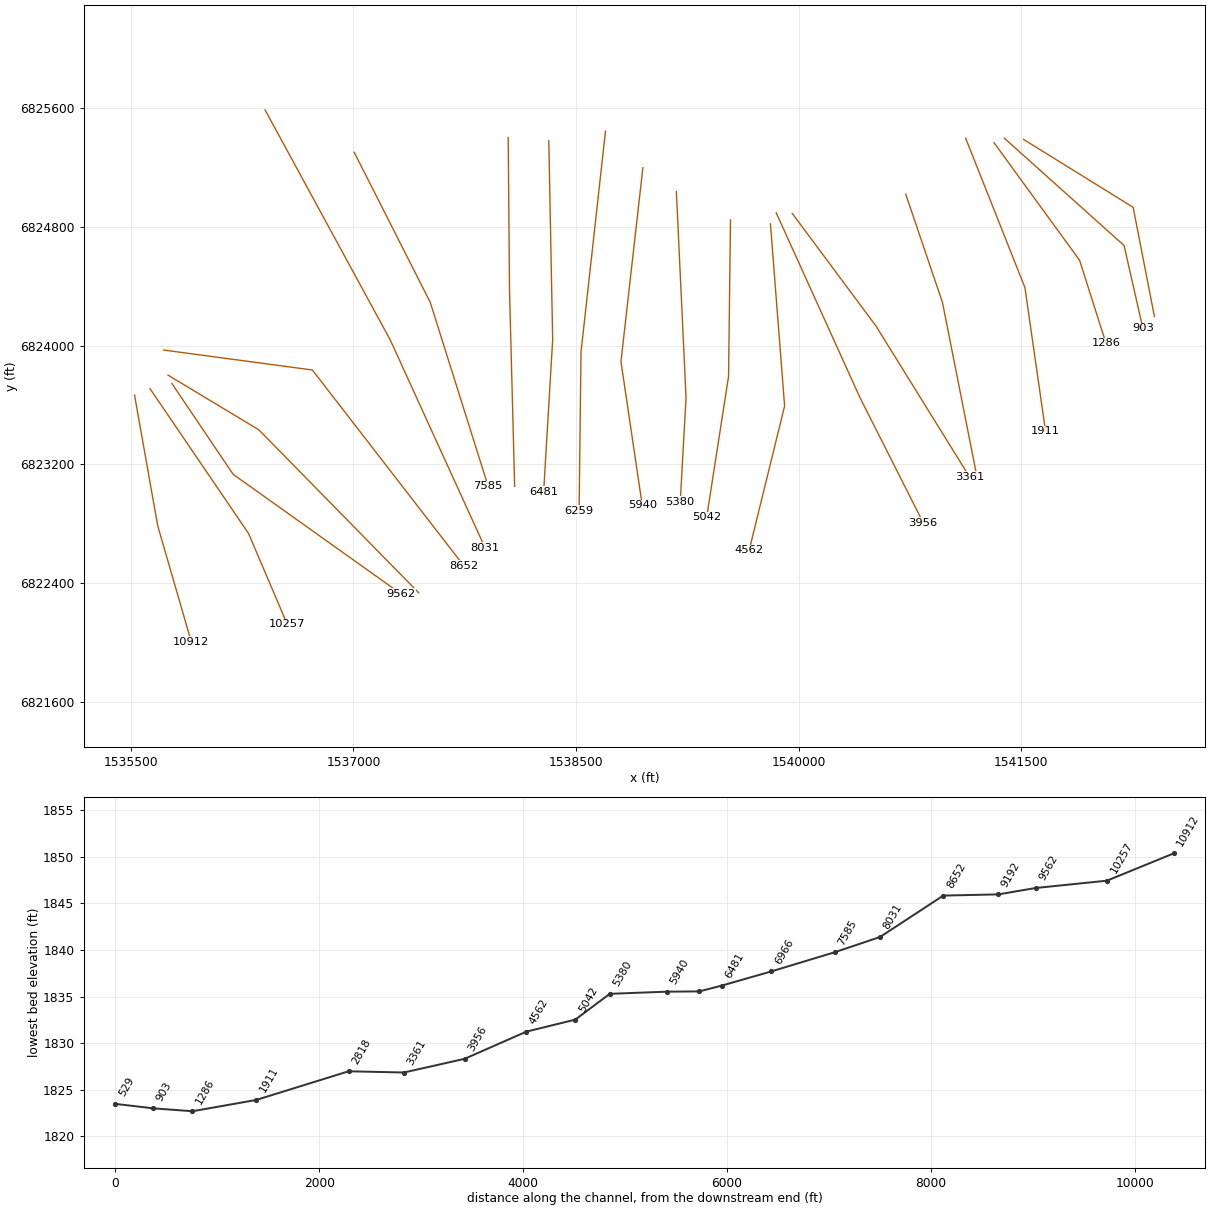
HEC-RAS study Elm 01 27.prj: Elm 01 27 Base Level Engineering

--- Elm 01 27.g01 (geometry) --- (continued)

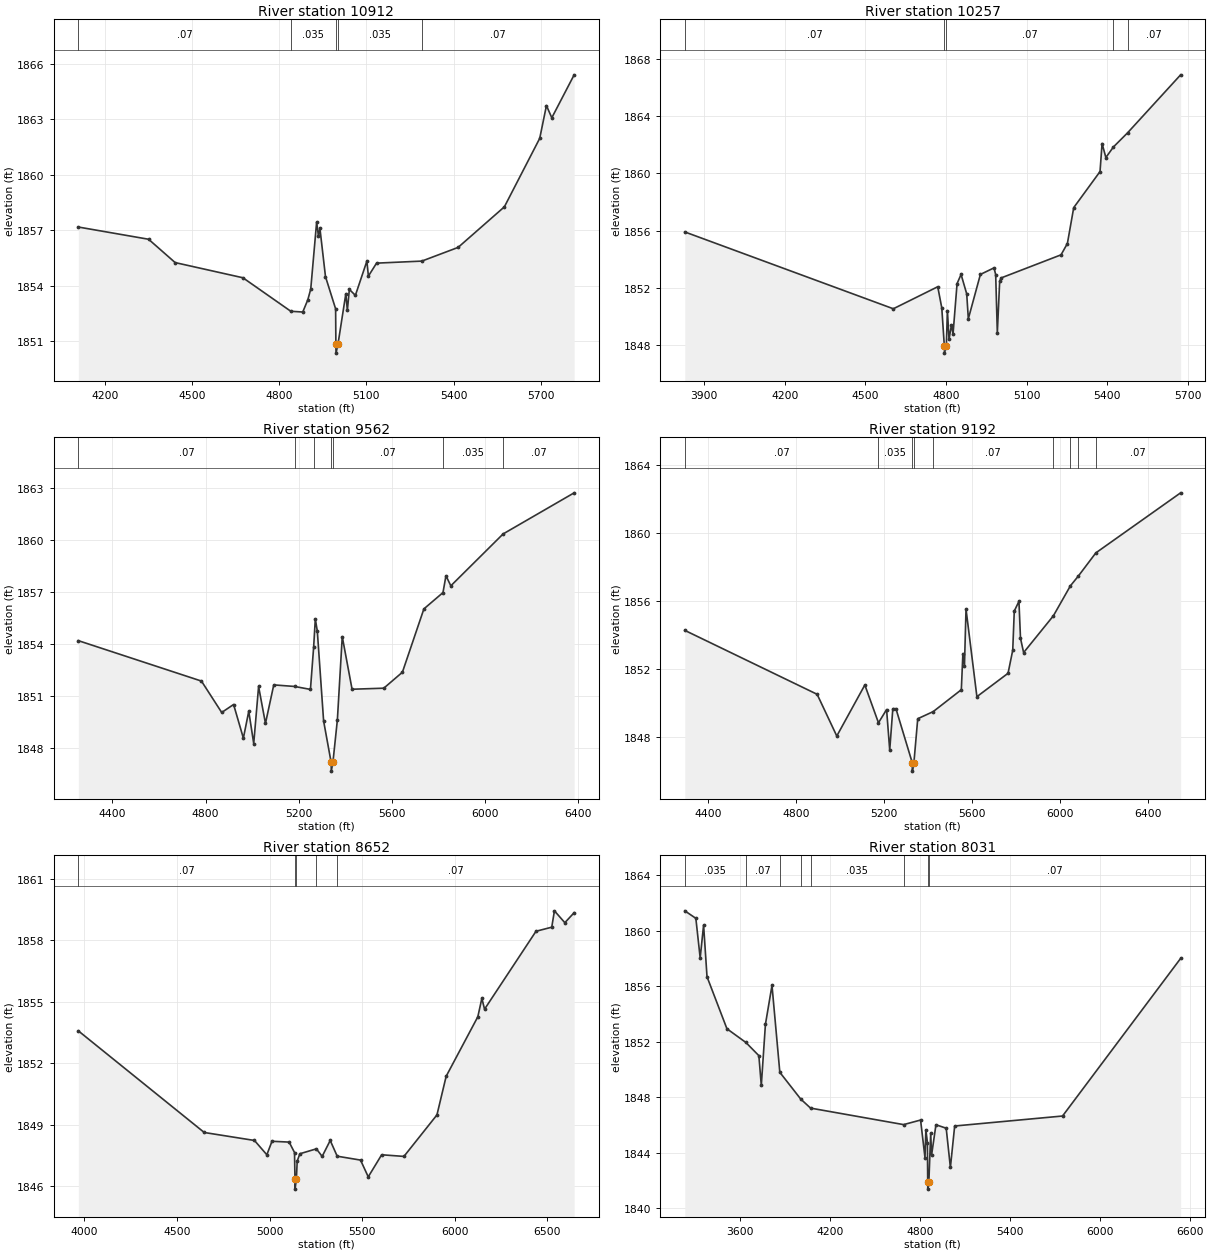
Type RM Length L Ch R = 1 ,10912   ,655,655,655
BEGIN DESCRIPTION:
Elm 01 27 10911.95
END DESCRIPTION:
XS GIS Cut Line= 3
      1535525.36      6823666.33      1535681.61      6822785.24
       1535907.3      6822004.02
#Sta/Elev= 30
  4107.6 1857.18  4349.6 1856.52  4441.1 1855.26  4674.6 1854.44  4839.6 1852.63
  4880.7 1852.59  4898.1 1853.25  4908.2 1853.83  4928.5 1857.45  4934.8 1856.69
  4939.8 1857.11    4959  1854.5  4993.9 1852.76  4994.8 1850.87  4995.3 1850.37
  5002.2 1850.87  5029.1 1853.58  5034.3 1852.68  5041.2 1853.81    5062 1853.49
  5101.6 1855.34  5106.8 1854.53  5134.9 1855.23  5290.8 1855.34  5415.9 1856.08
  5575.2 1858.27    5697 1861.97  5720.1 1863.74  5738.6 1863.08  5815.6  1865.4
#Mann= 5 ,-1 , 0
  4107.6     .07       0  4839.6    .035       0  4994.8    .035       0
  5002.2    .035       0  5290.8     .07       0
Bank Sta=4994.8,5002.2
XS Rating Curve= 0 ,0
Exp/Cntr=0.3,0.1

Type RM Length L Ch R = 1 ,10257   ,695,695,695
BEGIN DESCRIPTION:
Elm 01 27 10257.35
END DESCRIPTION:
XS GIS Cut Line= 3
      1535629.53      6823709.72      1536293.59      6822733.16
      1536553.64      6822122.04
#Sta/Elev= 30
  3827.7 1855.91  4603.7 1850.54    4769 1852.08    4784  1850.6  4793.5 1847.94
    4794 1847.44  4800.9 1847.94    4805 1850.41    4811  1848.4  4819.9 1849.41
  4825.9 1848.78  4840.9  1852.3  4855.8 1852.94  4876.8 1851.58  4882.8 1849.84
  4927.7 1852.94  4978.5  1853.4  4984.6 1852.92  4990.7 1848.86  4999.5 1852.48
  5005.5  1852.7  5227.8 1854.31  5251.4  1855.1    5275 1857.61  5372.9 1860.13
  5380.5 1862.09  5394.6 1861.11  5422.8 1861.85  5475.6 1862.84  5672.8 1866.89
#Mann= 5 ,-1 , 0
  3827.7     .07       0  4793.5     .07       0  4800.9     .07       0
  5422.8    .035       0  5475.6     .07       0
Bank Sta=4793.5,4800.9
XS Rating Curve= 0 ,0
Exp/Cntr=0.3,0.1

Type RM Length L Ch R = 1 ,9562    ,370,370,370
BEGIN DESCRIPTION:
Elm 01 27 9561.84
END DESCRIPTION:
XS GIS Cut Line= 3
      1535777.09      6823744.45      1536189.43      6823132.46
      1537321.12      6822325.97
#Sta/Elev= 30
  4254.2 1854.18  4782.5 1851.85  4869.4 1850.04  4920.4  1850.5  4962.4 1848.56
  4985.5 1850.11  5006.8 1848.25  5027.7 1851.54  5057.2 1849.41  5092.8 1851.63
  5181.8 1851.54  5250.2 1851.37    5264 1853.82  5271.1 1855.43  5279.7 1854.73
  5306.7 1849.55  5339.1 1847.16  5339.6 1846.66  5346.6 1847.16  5365.8 1849.62
  5386.7 1854.41  5428.8 1851.38  5564.9 1851.44  5644.8 1852.36    5737 1856.01
  5818.9 1856.95  5831.7 1857.92  5852.6 1857.34  6076.9 1860.33  6381.8  1862.7
#Mann= 7 ,-1 , 0
  4254.2     .07       0  5181.8    .035       0    5264     .07       0
  5339.1     .07       0  5346.6     .07       0  5818.9    .035       0
  6076.9     .07       0
Bank Sta=5339.1,5346.6
XS Rating Curve= 0 ,0
Exp/Cntr=0.3,0.1

Type RM Length L Ch R = 1 ,9192    ,540,540,540
BEGIN DESCRIPTION:
Elm 01 27 9191.56
END DESCRIPTION:
XS GIS Cut Line= 3
       1535751.1      6823800.84      1536363.04      6823431.94
      1537439.43      6822333.85
#Sta/Elev= 30
  4295.2 1854.27  4896.3  1850.5  4985.6 1848.04    5113 1851.05  5174.9 1848.82
  5211.8  1849.6    5226 1847.21  5240.1 1849.65  5254.3 1849.65  5328.3 1846.47
  5328.8 1845.97  5335.9 1846.47  5353.3 1849.06  5423.6 1849.48  5551.3 1850.77
  5558.4  1852.9  5565.5 1852.17  5572.6 1855.52    5622 1850.36  5763.5 1851.74
  5784.8  1853.1  5791.8 1855.41    5813 1855.98    5820 1853.81  5834.2 1852.96
  5969.5 1855.13  6046.9  1856.9  6082.1 1857.46  6162.4 1858.84  6547.4 1862.38
#Mann= 9 ,-1 , 0
  4295.2     .07       0  5174.9    .035       0  5328.3     .07       0
  5335.9    .035       0  5423.6     .07       0  5969.5    .035       0
  6046.9     .07       0  6082.1    .035       0  6162.4     .07       0
Bank Sta=5328.3,5335.9
XS Rating Curve= 0 ,0
Exp/Cntr=0.3,0.1

Type RM Length L Ch R = 1 ,8652    ,621,621,621
BEGIN DESCRIPTION:
Elm 01 27 8651.81
END DESCRIPTION:
XS GIS Cut Line= 3
      1535720.65      6823970.14      1536723.28      6823835.59
      1537743.23      6822516.16
#Sta/Elev= 30
  3966.8 1853.58  4647.2 1848.61  4918.6 1848.22  4985.5 1847.52  5013.3 1848.18
    5106 1848.14    5135 1847.63  5137.5 1846.34    5138 1845.84  5145.1 1846.34
  5149.5 1847.21  5163.9 1847.57  5253.1 1847.81  5284.4 1847.44  5327.9 1848.22
  5365.7 1847.45  5491.8 1847.26  5533.4 1846.44  5605.9 1847.52  5726.3 1847.44
  5904.7 1849.47  5954.5 1851.36  6125.6 1854.27  6147.4 1855.17  6161.9 1854.64
  6439.9 1858.45    6525 1858.65  6539.5 1859.45  6595.7 1858.87  6646.1 1859.36
#Mann= 5 ,-1 , 0
  3966.8     .07       0  5137.5     .07       0  5145.1     .07       0
  5253.1    .035       0  5365.7     .07       0
Bank Sta=5137.5,5145.1
XS Rating Curve= 0 ,0
Exp/Cntr=0.3,0.1

Type RM Length L Ch R = 1 ,8031    ,446,446,446
BEGIN DESCRIPTION:
Elm 01 27 8031.203
END DESCRIPTION:
XS GIS Cut Line= 3
        1536405.      6825588.01      1537249.25      6824035.51
      1537886.46       6822637.7
#Sta/Elev= 30
  3232.8 1861.45  3306.4 1860.91  3335.3 1858.05    3358 1860.42  3380.8  1856.7
  3513.5 1852.95  3639.9 1851.96  3726.3 1851.01  3742.5 1848.86    3770 1853.27
  3813.7 1856.07  3865.9 1849.81  4005.3 1847.88  4070.7 1847.23  4690.7 1846.04
  4803.7 1846.37  4833.1 1843.65  4838.8 1845.67  4849.2 1844.75  4851.2 1841.89
  4851.7 1841.39  4858.8 1841.89  4871.1 1845.43  4876.8 1843.83  4906.1 1846.03
  4974.4 1845.78  5002.3 1842.95  5030.8 1845.94  5749.6 1846.66  6536.2 1858.02
#Mann= 8 ,-1 , 0
  3232.8    .035       0  3639.9     .07       0  3865.9    .035       0
  4005.3     .07       0  4070.7    .035       0  4690.7     .07       0
  4851.2     .07       0  4858.8     .07       0
Bank Sta=4851.2,4858.8
XS Rating Curve= 0 ,0
Exp/Cntr=0.3,0.1

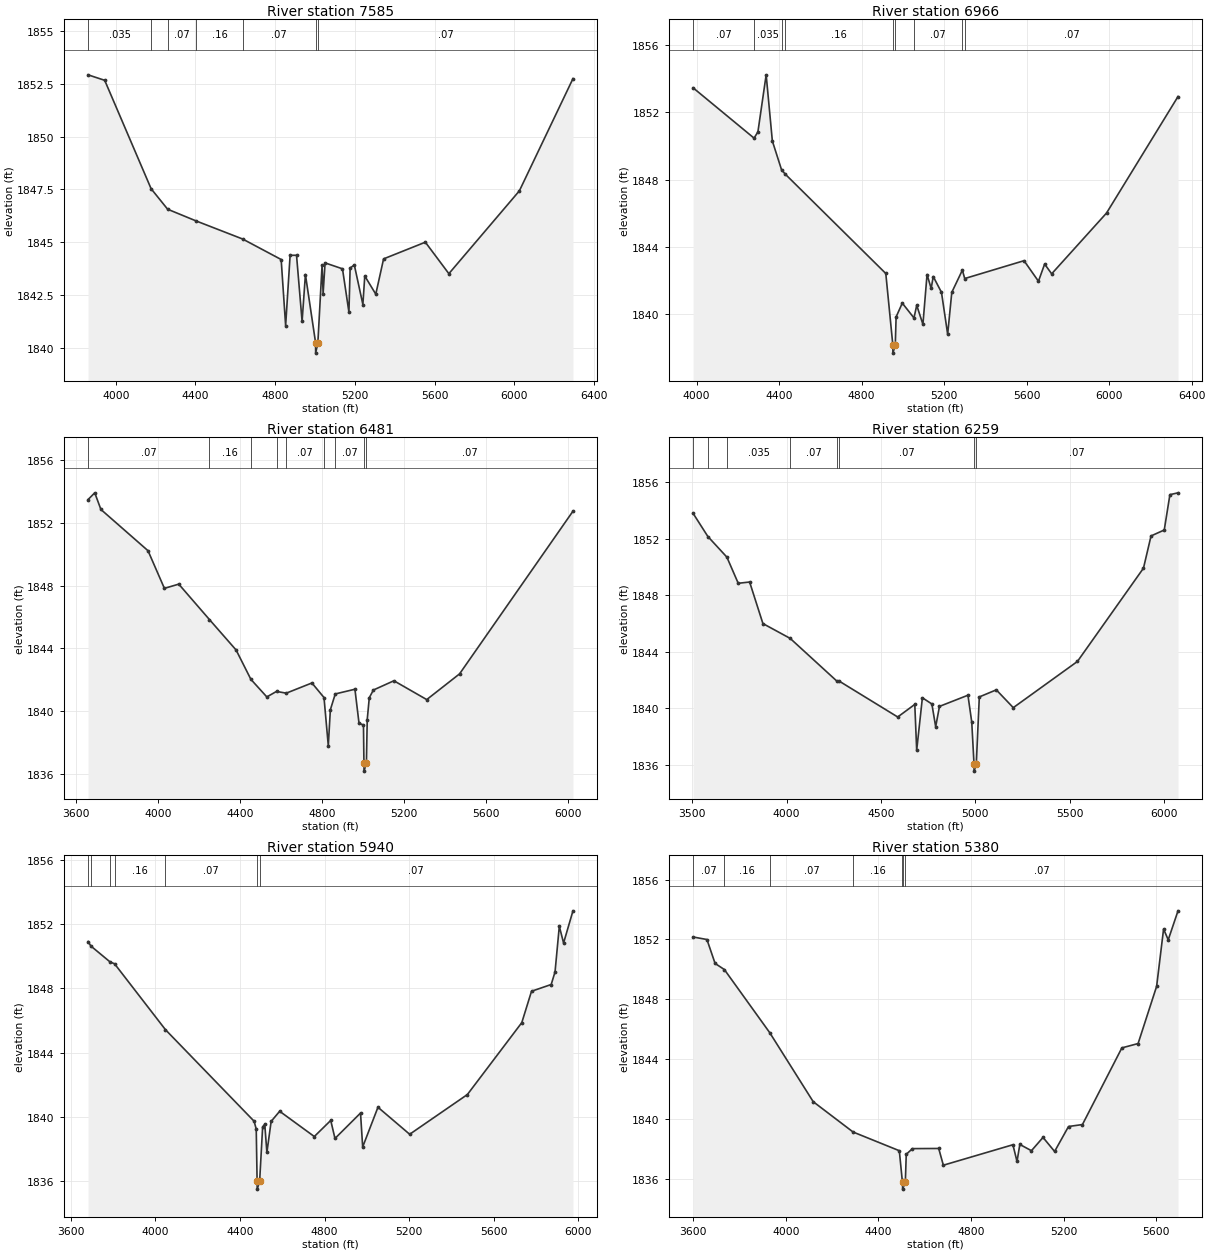
Type RM Length L Ch R = 1 ,7585    ,619,619,619
BEGIN DESCRIPTION:
Elm 01 27 7584.89
END DESCRIPTION:
XS GIS Cut Line= 3
      1537005.41      6825302.57      1537517.55      6824291.32
       1537907.7       6823051.5
#Sta/Elev= 30
  3861.1 1852.92  3944.7 1852.66  4177.6 1847.53  4260.5 1846.56  4404.9    1846
  4636.9 1845.15  4830.2 1844.18  4852.6 1841.05  4875.1 1844.38  4907.3 1844.38
  4935.2 1841.25  4951.9 1843.47  5002.8 1840.25  5003.3 1839.75  5014.4 1840.25
  5035.5 1843.92  5040.7 1842.57  5050.5 1844.02  5137.9 1843.74  5170.2 1841.69
  5176.3 1843.78  5197.3 1843.92  5240.2 1842.05  5249.7  1843.4    5305 1842.54
  5344.1 1844.21  5553.7    1845  5671.7 1843.51  6025.5 1847.43  6294.4 1852.74
#Mann= 7 ,-1 , 0
  3861.1    .035       0  4177.6     .16       0  4260.5     .07       0
  4404.9     .16       0  4636.9     .07       0  5002.8     .07       0
  5014.4     .07       0
Bank Sta=5002.8,5014.4
XS Rating Curve= 0 ,0
Exp/Cntr=0.3,0.1

Type RM Length L Ch R = 1 ,6966    ,485,485,485
BEGIN DESCRIPTION:
Elm 01 27 6965.92
END DESCRIPTION:
XS GIS Cut Line= 3
      1538042.72      6825402.43      1538051.41      6824373.78
      1538086.09      6823051.52
#Sta/Elev= 30
  3982.5 1853.46  4278.2 1850.47  4296.9 1850.84  4336.9 1854.23  4366.9  1850.3
  4411.5 1848.59  4429.6 1848.33    4917 1842.43    4951  1838.2  4951.5  1837.7
    4963  1838.2    4967 1839.85    4997 1840.67  5053.6 1839.79    5067 1840.54
    5097 1839.41    5117 1842.37    5137 1841.54    5147 1842.25    5187 1841.31
    5217 1838.82    5237 1841.31  5288.3 1842.63  5299.7 1842.13  5587.2 1843.19
  5657.2 1841.97  5687.2 1842.99  5721.3 1842.41  5987.3 1846.02  6333.9 1852.94
#Mann= 9 ,-1 , 0
  3982.5     .07       0  4278.2    .035       0  4411.5     .07       0
  4429.6     .16       0    4951     .07       0    4963     .16       0
  5053.6     .07       0  5288.3     .16       0  5299.7     .07       0
Bank Sta=4951,4963
XS Rating Curve= 0 ,0
Exp/Cntr=0.3,0.1

Type RM Length L Ch R = 1 ,6481    ,222,222,222
BEGIN DESCRIPTION:
Elm 01 27 6481.14
END DESCRIPTION:
XS GIS Cut Line= 3
      1538316.16      6825380.77       1538342.2      6824039.58
      1538281.44      6823015.32
#Sta/Elev= 30
    3657 1853.49  3689.8 1853.92  3719.8 1852.86  3949.8 1850.23  4029.8 1847.83
  4099.9  1848.1  4249.8 1845.84  4379.9  1843.9  4452.1 1842.03  4529.9 1840.91
  4577.1 1841.26  4624.9 1841.15    4750  1841.8    4809 1840.87    4830  1837.8
    4840 1840.09    4864  1841.1    4960  1841.4    4980 1839.23  5001.7 1839.12
    5004 1836.68  5004.5 1836.18    5016 1836.68  5020.1 1839.47  5030.1 1840.86
  5050.1 1841.35  5150.3 1841.94  5310.6 1840.74  5470.9 1842.38  6024.5 1852.75
#Mann= 9 ,-1 , 0
    3657     .07       0  4249.8     .16       0  4452.1     .07       0
  4577.1     .16       0  4624.9     .07       0    4809     .16       0
    4864     .07       0    5004     .07       0    5016     .07       0
Bank Sta=5004,5016
XS Rating Curve= 0 ,0
Exp/Cntr=0.3,0.1

Type RM Length L Ch R = 1 ,6259    ,319,319,319
BEGIN DESCRIPTION:
Elm 01 27 6259.36
END DESCRIPTION:
XS GIS Cut Line= 3
      1538698.11      6825445.87      1538533.18      6823957.12
      1538520.16      6822885.06
#Sta/Elev= 30
  3504.1 1853.79  3582.5 1852.15  3683.3 1850.69  3743.4 1848.84  3803.8 1848.93
  3874.2 1845.99  4018.8 1844.94  4266.9 1841.91  4277.1 1841.93  4588.6 1839.38
  4679.1 1840.27  4689.2 1837.03  4719.4 1840.74  4769.7  1840.3  4789.8 1838.69
  4809.9 1840.13  4960.8 1840.92    4981 1839.02    4993 1836.05  4993.5 1835.55
    5005 1836.05  5021.1  1840.8  5111.1  1841.3  5201.1 1840.04  5541.1 1843.31
  5891.1 1849.91  5931.2 1852.19  6001.2 1852.61  6031.2 1855.11  6074.1 1855.24
#Mann= 8 ,-1 , 0
  3504.1     .16       0  3582.5     .07       0  3683.3    .035       0
  4018.8     .07       0  4266.9    .035       0  4277.1     .07       0
    4993     .07       0    5005     .07       0
Bank Sta=4993,5005
XS Rating Curve= 0 ,0
Exp/Cntr=0.3,0.1

Type RM Length L Ch R = 1 ,5940    ,560,560,560
BEGIN DESCRIPTION:
Elm 01 27 5939.7
END DESCRIPTION:
XS GIS Cut Line= 3
      1538949.84      6825198.45      1538802.27      6823892.01
      1538945.51       6822924.1
#Sta/Elev= 30
  3681.2 1850.91  3694.8 1850.63  3785.7 1849.64  3806.5 1849.53  4047.4 1845.43
  4466.6 1839.74  4476.6 1839.25  4480.7 1836.02  4481.2 1835.52  4492.7 1836.02
  4506.9 1839.39  4516.9 1839.55    4527  1837.8  4547.1 1839.73  4587.4 1840.36
  4751.2 1838.79  4828.9 1839.79    4849 1838.67  4969.8 1840.25  4979.9 1838.14
  5052.2 1840.61  5202.2 1838.93  5475.1  1841.4  5732.4 1845.87  5778.4 1847.82
  5871.4 1848.24  5889.6 1849.02  5909.8 1851.86    5930 1850.82  5974.4 1852.82
#Mann= 7 ,-1 , 0
  3681.2     .07       0  3694.8     .16       0  3785.7     .07       0
  3806.5     .16       0  4047.4     .07       0  4480.7     .07       0
  4492.7     .07       0
Bank Sta=4480.7,4492.7
XS Rating Curve= 0 ,0
Exp/Cntr=0.3,0.1

Type RM Length L Ch R = 1 ,5380    ,338,338,338
BEGIN DESCRIPTION:
Elm 01 27 5380.36
END DESCRIPTION:
XS GIS Cut Line= 3
      1539175.54      6825037.82      1539240.64      6823648.96
      1539201.58      6822945.83
#Sta/Elev= 30
  3599.2 1852.16  3659.1 1851.99  3694.3 1850.39  3734.4 1849.98  3930.2 1845.76
  4118.1 1841.14  4290.4 1839.11    4490 1837.86  4502.4 1835.92  4503.9 1835.79
  4504.4 1835.29  4516.1 1835.79    4520 1837.62  4546.9    1838  4660.2 1838.01
  4680.2 1836.89  4980.7 1838.26  4998.4 1837.14  5010.6 1838.28  5060.7 1837.86
  5110.7 1838.75  5160.8 1837.81  5220.9 1839.48    5281 1839.61  5451.3 1844.74
  5521.4 1845.03  5601.5 1848.86  5631.5 1852.69  5651.6 1851.97  5693.8 1853.91
#Mann= 7 ,-1 , 0
  3599.2     .07       0  3734.4     .16       0  3930.2     .07       0
  4290.4     .16       0  4502.4     .07       0  4503.9     .07       0
  4516.1     .07       0
Bank Sta=4503.9,4516.1
XS Rating Curve= 0 ,0
Exp/Cntr=0.3,0.1

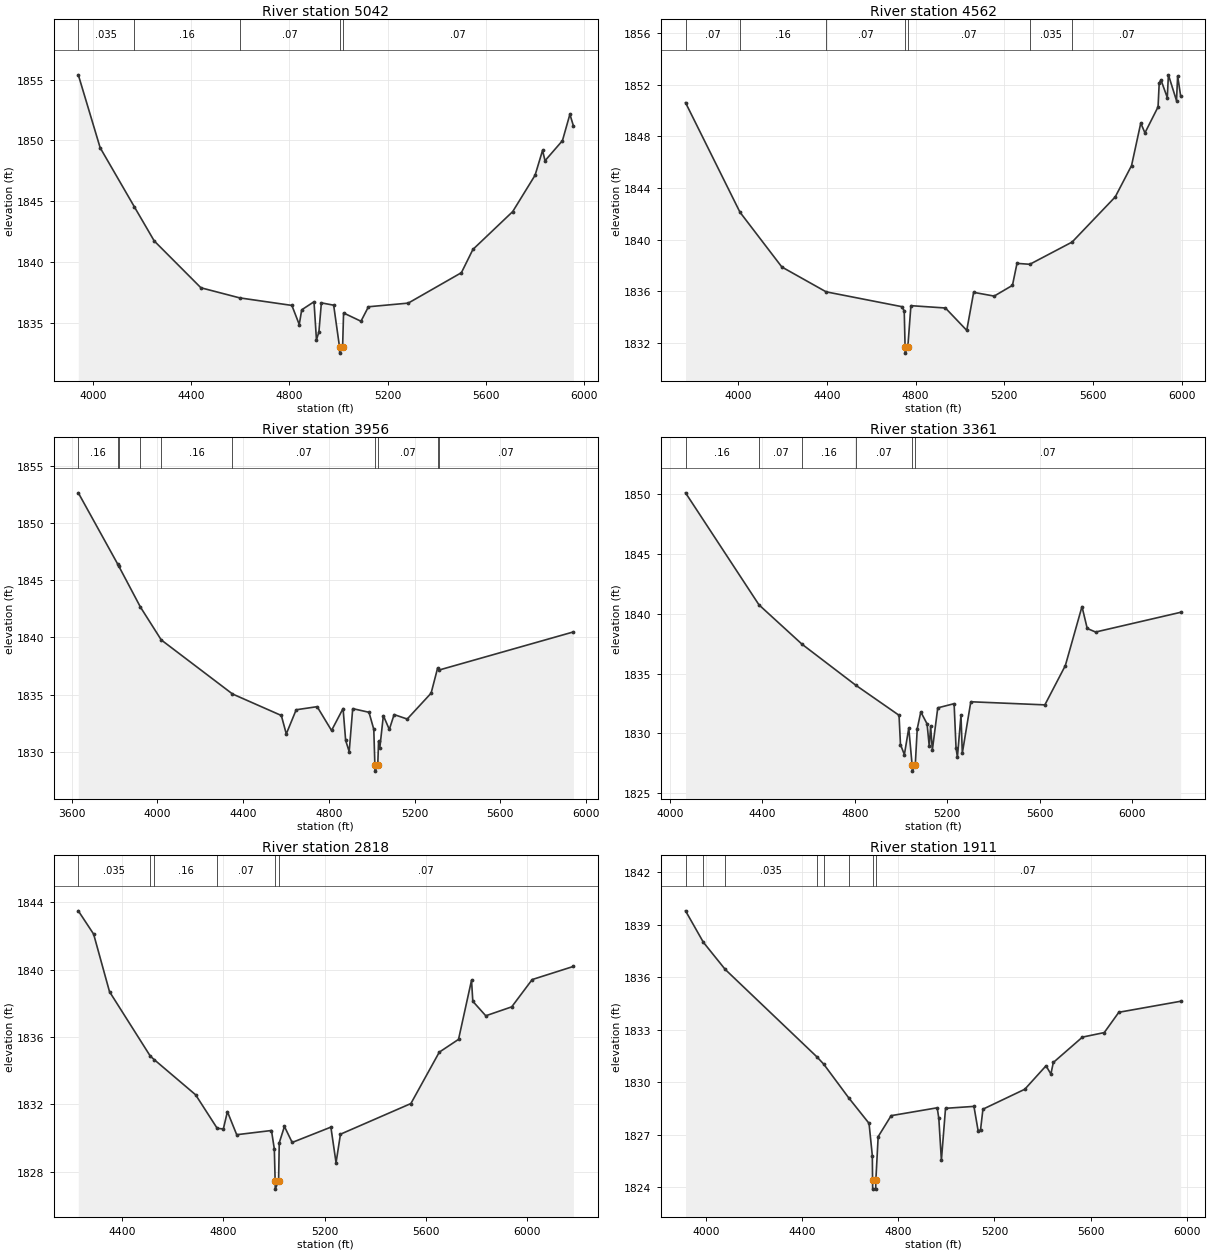
Type RM Length L Ch R = 1 ,5042    ,480,480,480
BEGIN DESCRIPTION:
Elm 01 27 5042.05
END DESCRIPTION:
XS GIS Cut Line= 3
      1539540.12      6824846.91       1539527.1      6823792.19
      1539379.87      6822843.85
#Sta/Elev= 30
    3941 1855.39  4029.9  1849.4  4169.2 1844.54  4249.9 1841.74  4439.9 1837.89
  4597.6 1837.06    4810 1836.44    4840 1834.87    4850 1836.08    4900 1836.74
    4910 1833.61    4920 1834.27    4930 1836.65    4980 1836.46  5003.9 1833.02
  5004.4 1832.52  5016.4 1833.02  5020.3 1835.82  5091.1 1835.14  5121.5 1836.33
  5283.4 1836.63  5499.7 1839.13  5546.5 1841.04  5708.4 1844.15  5799.5 1847.14
  5829.9 1849.18    5840 1848.33  5910.8 1849.98  5941.2 1852.15  5955.5 1851.19
#Mann= 5 ,-1 , 0
    3941    .035       0  4169.2     .16       0  4597.6     .07       0
  5003.9     .07       0  5016.4     .07       0
Bank Sta=5003.9,5016.4
XS Rating Curve= 0 ,0
Exp/Cntr=0.3,0.1

Type RM Length L Ch R = 1 ,4562    ,606,606,606
BEGIN DESCRIPTION:
Elm 01 27 4562.19
END DESCRIPTION:
XS GIS Cut Line= 3
      1539809.21      6824820.88       1539904.7      6823592.53
      1539666.31      6822621.62
#Sta/Elev= 30
  3763.4  1850.6  4008.7 1842.13  4197.6 1837.89  4397.1 1835.97  4739.2 1834.82
  4749.2 1834.48    4753 1831.73  4753.5 1831.23  4765.5 1831.73  4779.3  1834.9
  4934.8 1834.72    5031 1832.99  5062.1 1835.93  5154.6 1835.64    5237 1836.47
  5257.5 1838.17  5315.3  1838.1    5506 1839.82  5700.3 1843.31  5773.8 1845.73
  5815.4 1849.02  5834.2 1848.26  5893.3 1850.27  5898.5 1852.11  5906.3 1852.36
  5934.9 1850.99    5940 1852.75  5976.5 1850.75  5981.6 1852.67  5995.2 1851.11
#Mann= 7 ,-1 , 0
  3763.4     .07       0  4008.7     .16       0  4397.1     .07       0
    4753     .07       0  4765.5     .07       0  5315.3    .035       0
    5506     .07       0
Bank Sta=4753,4765.5
XS Rating Curve= 0 ,0
Exp/Cntr=0.3,0.1

Type RM Length L Ch R = 1 ,3956    ,595,595,595
BEGIN DESCRIPTION:
Elm 01 27 3956.05
END DESCRIPTION:
XS GIS Cut Line= 3
      1539848.29      6824894.59      1540412.52      6823648.96
      1540837.86      6822806.95
#Sta/Elev= 30
  3630.8 1852.62  3814.6  1846.4  3820.2  1846.2  3920.8 1842.64    4018 1839.77
  4350.4 1835.05  4578.4 1833.17  4601.5 1831.56  4647.7 1833.67  4745.6 1833.94
  4812.7 1831.86  4866.5 1833.78  4878.6 1830.99  4895.1 1830.01  4911.5 1833.77
  4987.5 1833.45  5009.9 1831.96    5015 1828.81  5015.5 1828.31  5028.4 1828.81
  5032.2 1830.92  5037.8  1830.3  5054.5 1833.16  5082.4 1831.95  5104.7 1833.25
  5165.9 1832.86  5277.4 1835.12    5308 1837.33  5314.3 1837.14  5941.6 1840.47
#Mann= 10 ,-1 , 0
  3630.8     .16       0  3814.6     .07       0  3820.2     .16       0
  3920.8     .07       0    4018     .16       0  4350.4     .07       0
    5015     .07       0  5028.4     .07       0    5308    .035       0
  5314.3     .07       0
Bank Sta=5015,5028.4
XS Rating Curve= 0 ,0
Exp/Cntr=0.3,0.1

Type RM Length L Ch R = 1 ,3361    ,543,543,543
BEGIN DESCRIPTION:
Elm 01 27 3360.56
END DESCRIPTION:
XS GIS Cut Line= 3
      1539956.76      6824890.31      1540521.02      6824130.73
      1541150.18      6823115.39
#Sta/Elev= 30
  4068.2 1850.11  4385.9 1840.74    4572 1837.45  4803.8 1834.03  4991.3 1831.51
  4997.5 1829.06  5014.4 1828.22  5033.4 1830.44  5047.9 1827.34  5048.4 1826.84
  5061.4 1827.34    5070 1830.38  5085.4 1831.79  5112.5 1830.79    5122 1828.91
  5127.9  1830.6  5135.3  1828.6  5158.7 1832.13  5229.4 1832.48  5237.8 1828.76
  5243.7 1828.01  5259.1 1831.51  5264.9 1828.34  5301.6 1832.64  5621.8 1832.38
  5710.4 1835.67  5782.3  1840.6  5804.9 1838.77  5841.1 1838.47  6208.9 1840.12
#Mann= 6 ,-1 , 0
  4068.2     .16       0  4385.9     .07       0    4572     .16       0
  4803.8     .07       0  5047.9     .07       0  5061.4     .07       0
Bank Sta=5047.9,5061.4
XS Rating Curve= 0 ,0
Exp/Cntr=0.3,0.1

Type RM Length L Ch R = 1 ,2818    ,907,907,907
BEGIN DESCRIPTION:
Elm 01 27 2818.05
END DESCRIPTION:
XS GIS Cut Line= 3
      1540720.67      6825020.51      1540968.07      6824291.32
       1541198.1      6823128.17
#Sta/Elev= 30
  4226.9 1843.49  4287.4 1842.11  4350.2 1838.69  4511.1 1834.87  4526.5 1834.66
  4690.3 1832.57  4775.5 1830.58  4799.8 1830.54  4815.9 1831.57  4852.6  1830.2
  4989.9 1830.45  5001.2 1829.35  5004.4 1827.47  5004.9 1826.97    5018 1827.47
  5020.7 1829.72  5041.1 1830.69  5071.7 1829.74  5224.6 1830.65    5245 1828.54
  5262.4 1830.23  5540.6 1832.05  5652.7  1835.1  5728.8 1835.86  5780.1 1839.37
  5785.2 1838.12  5836.4 1837.26  5938.9 1837.79  6019.7 1839.41  6182.6 1840.19
#Mann= 6 ,-1 , 0
  4226.9    .035       0  4511.1     .07       0  4526.5     .16       0
  4775.5     .07       0  5004.4     .07       0    5018     .07       0
Bank Sta=5004.4,5018
XS Rating Curve= 0 ,0
Exp/Cntr=0.3,0.1

Type RM Length L Ch R = 1 ,1911    ,625,625,625
BEGIN DESCRIPTION:
Elm 01 27 1910.89
END DESCRIPTION:
XS GIS Cut Line= 3
       1541124.3      6825398.13      1541523.63      6824391.14
      1541662.52      6823423.23
#Sta/Elev= 30
  3914.2  1839.8  3988.5    1838  4079.4 1836.45  4461.2 1831.45  4489.2 1831.04
  4593.4 1829.11  4678.1 1827.65  4691.7 1825.81  4692.8 1824.39  4693.3 1823.89
  4705.9 1823.89  4706.4 1824.39  4716.1 1826.89  4770.1 1828.09  4961.9 1828.54
  4968.6 1827.93  4979.3 1825.54  4996.5 1828.51  5114.8 1828.62    5132 1827.24
  5142.1 1827.26  5152.2 1828.46  5326.5  1829.6  5414.8 1830.94  5435.1 1830.47
  5445.2 1831.13  5566.4 1832.58  5657.3 1832.84  5717.9    1834  5975.3 1834.63
#Mann= 8 ,-1 , 0
  3914.2    .035       0  3988.5     .07       0  4079.4    .035       0
  4461.2     .07       0  4489.2    .035       0  4593.4     .07       0
  4692.8     .07       0  4706.4     .07       0
Bank Sta=4692.8,4706.4
XS Rating Curve= 0 ,0
Exp/Cntr=0.3,0.1

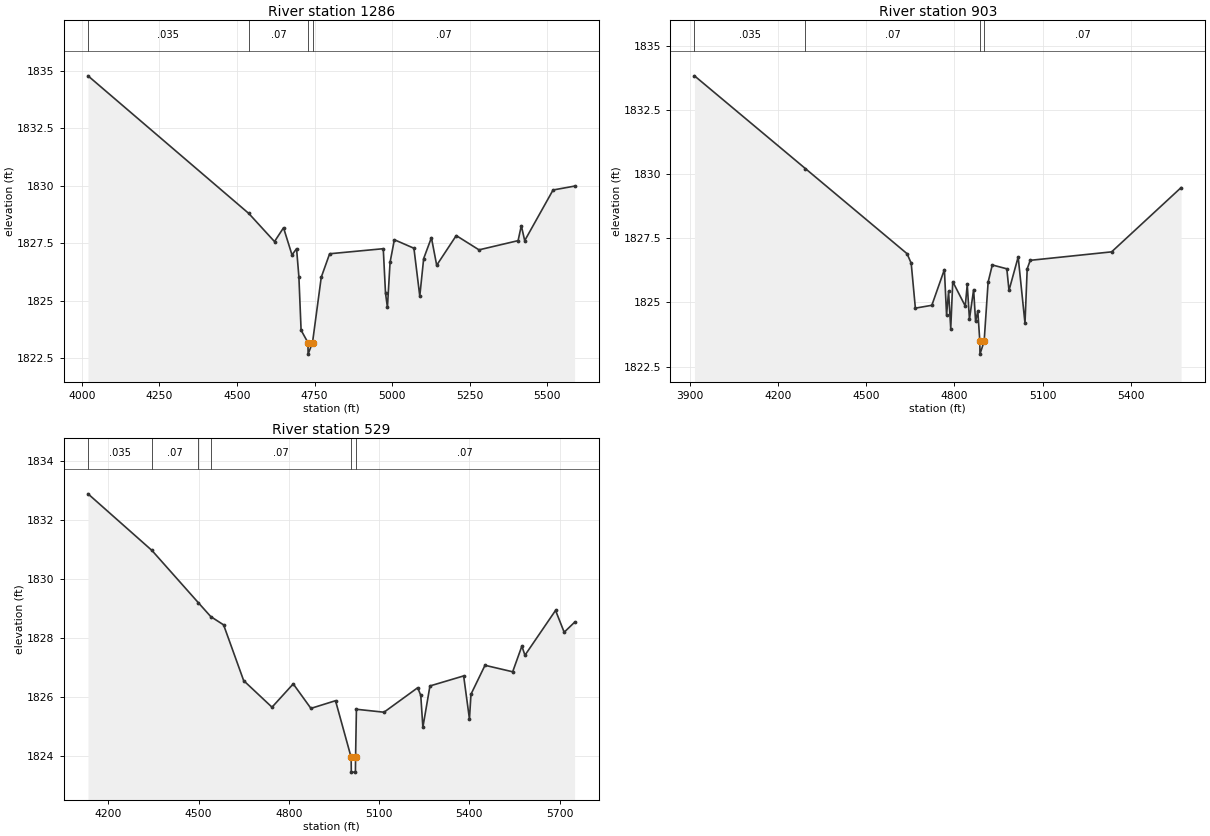
Type RM Length L Ch R = 1 ,1286    ,383,383,383
BEGIN DESCRIPTION:
Elm 01 27 1285.856
END DESCRIPTION:
XS GIS Cut Line= 3
       1541315.3       6825367.7      1541891.97      6824574.96
      1542070.25      6824014.32
#Sta/Elev= 30
  4019.7 1834.77  4538.1 1828.79  4620.9 1827.57    4650 1828.17  4677.3 1826.99
    4692 1827.26  4699.5 1826.04  4706.6 1823.72  4728.7 1823.18  4729.2 1822.68
  4743.4 1823.18  4771.6 1826.02  4798.6 1827.04  4971.5 1827.26  4978.7 1825.33
  4984.9 1824.71  4993.4 1826.67  5007.3 1827.65  5070.3 1827.28  5089.2  1825.2
  5101.7 1826.83  5126.7 1827.74  5143.7 1826.54  5206.7 1827.83  5280.1 1827.21
  5406.1 1827.61  5416.5 1828.26  5427.4 1827.61  5518.8 1829.81  5588.3 1829.98
#Mann= 4 ,-1 , 0
  4019.7    .035       0  4538.1     .07       0  4728.7     .07       0
  4743.4     .07       0
Bank Sta=4728.7,4743.4
XS Rating Curve= 0 ,0
Exp/Cntr=0.3,0.1

Type RM Length L Ch R = 1 ,903     ,374,374,374
BEGIN DESCRIPTION:
Elm 01 27 902.854
END DESCRIPTION:
XS GIS Cut Line= 3
      1541384.74      6825398.09       1542191.6      6824674.64
       1542317.9      6824117.68
#Sta/Elev= 30
  3916.3 1833.82  4293.6 1830.21  4639.1  1826.9  4653.3 1826.53  4667.5 1824.78
  4723.5 1824.89  4766.2 1826.28  4773.6 1824.51  4780.4 1825.43  4787.8 1823.98
  4794.6 1825.81  4837.2 1824.86  4843.9  1825.7  4851.4 1824.35  4865.6  1825.5
  4872.3 1824.26  4879.8 1824.67  4886.7 1823.49  4887.2 1822.99  4901.4 1823.49
  4914.9 1825.79  4929.1 1826.46  4978.5 1826.31  4985.9 1825.47  5017.1 1826.77
  5040.3 1824.19  5047.8 1826.31  5058.1 1826.64  5334.9 1826.97  5571.1 1829.47
#Mann= 4 ,-1 , 0
  3916.3    .035       0  4293.6     .07       0  4886.7     .07       0
  4901.4     .07       0
Bank Sta=4886.7,4901.4
XS Rating Curve= 0 ,0
Exp/Cntr=0.3,0.1

Type RM Length L Ch R = 1 ,529     ,0,0,0
BEGIN DESCRIPTION:
Elm 01 27 528.549
END DESCRIPTION:
XS GIS Cut Line= 3
      1541514.91      6825389.43      1542252.72      6824932.18
      1542396.03       6824195.8
#Sta/Elev= 30
    4132  1832.9  4344.8 1830.98    4499 1829.21  4540.3 1828.74  4582.9 1828.46
  4649.7 1826.57  4743.9 1825.67  4814.5 1826.46  4873.3 1825.63  4955.1 1825.89
  5007.1 1823.97  5007.6 1823.47  5021.3 1823.47  5021.8 1823.97  5024.6  1825.6
  5116.3  1825.5  5228.4 1826.33  5238.6 1826.07  5245.6 1824.99  5269.1 1826.39
  5381.2 1826.73  5400.5 1825.27  5405.6 1826.11  5452.2 1827.09  5544.2 1826.87
  5574.8 1827.74    5585 1827.43  5686.8 1828.95  5715.5 1828.21  5750.2 1828.55
#Mann= 6 ,-1 , 0
    4132    .035       0  4344.8     .07       0    4499    .035       0
  4540.3     .07       0  5007.1     .07       0  5021.8     .07       0
Bank Sta=5007.1,5021.8
XS Rating Curve= 0 ,0
Exp/Cntr=0.3,0.1

Chan Stop Cuts=-1
Use User Specified Reach Order=0
Composite Channel Slope=5