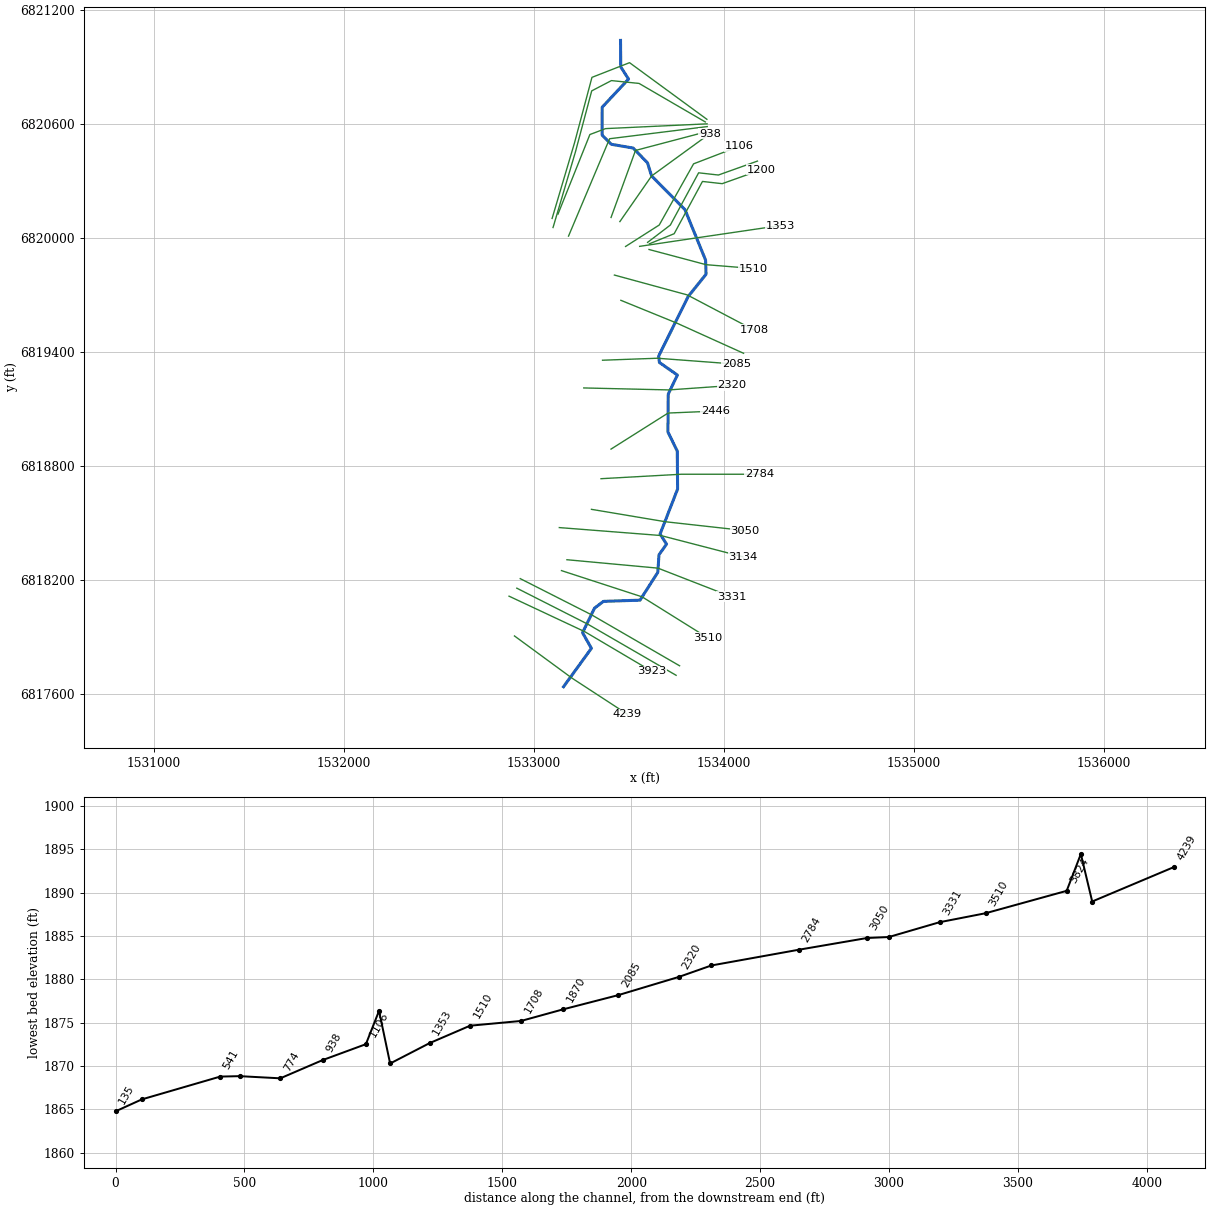
--- Elm 01 28.prj (project) ---

Proj Title=Elm 01 28 Base Level Engineering
Current Plan=p01
Default Exp/Contr=0.3,0.1
English Units
Geom File=g01
Flow File=f01
Plan File=p01
BEGIN DESCRIPTION:
Elm 01 28
END DESCRIPTION:

--- Elm 01 28.p01 (plan) ---

Plan Title=Multiple Run
Short Identifier=Multiple
Geom File=g01
Flow File=f01
Subcritical Flow
K Sum by GR= 0
Std Step Tol= 0.01
Critical Tol= 0.01
Num of Std Step Trials= 20
Max Error Tol= 0.3
Flow Tol Ratio= 0.001
Split Flow NTrial= 30
Split Flow Tol= 0.02
Split Flow Ratio= 0.02
Log Output Level= 0
Friction Slope Method= 1
Unsteady Friction Slope Method= 2
Unsteady Bridges Friction Slope Method= 1
Parabolic Critical Depth
Global Vel Dist=  1 , 1 , 1
Global Log Level= 0
CheckData=True
Encroach Param= -1, 0, 0, 0
BEGIN DESCRIPTION:
Multiple Run
END DESCRIPTION:

--- Elm 01 28.f01 (steady flow) ---

Flow Title=Multiple
Number of Profiles=7
Profile Names=10-year,25-year,50-year,1pct_min,100-year,1pct_plu,500-year
River Rch & RM= Elm 01 28,Reach-1,4239
     158     212     256     191     306     421     444
Boundary for River Rch & Prof#=Elm 01 28,Reach-1,1
Up Type=0
Dn Type=3
Dn Slope=0.005
Boundary for River Rch & Prof#=Elm 01 28,Reach-1,2
Up Type=0
Dn Type=3
Dn Slope=0.005
Boundary for River Rch & Prof#=Elm 01 28,Reach-1,3
Up Type=0
Dn Type=3
Dn Slope=0.005
Boundary for River Rch & Prof#=Elm 01 28,Reach-1,4
Up Type=0
Dn Type=3
Dn Slope=0.005
Boundary for River Rch & Prof#=Elm 01 28,Reach-1,5
Up Type=0
Dn Type=3
Dn Slope=0.005
Boundary for River Rch & Prof#=Elm 01 28,Reach-1,6
Up Type=0
Dn Type=3
Dn Slope=0.005
Boundary for River Rch & Prof#=Elm 01 28,Reach-1,7
Up Type=0
Dn Type=3
Dn Slope=0.005

--- Elm 01 28.g01 (geometry) ---

Geom Title=Existing Conditions

River Reach=Elm 01 28,Reach-1
Reach XY= 30
      1533155.00      6817638.00      1533301.75      6817840.07
      1533255.03      6817922.29      1533318.44      6818051.64
      1533365.28      6818087.01      1533557.70      6818093.36
      1533651.18      6818239.58      1533657.54      6818332.11
      1533697.21      6818388.10      1533663.28      6818441.22
      1533755.45      6818677.81      1533753.78      6818877.50
      1533704.55      6818977.81      1533706.24      6819177.50
      1533754.44      6819277.52      1533659.81      6819343.62
      1533655.55      6819376.92      1533810.85      6819690.29
      1533905.21      6819808.05      1533902.84      6819882.02
      1533794.24      6820147.68      1533618.63      6820324.79
      1533596.85      6820394.07      1533521.79      6820471.56
      1533406.25      6820491.51      1533358.43      6820539.23
      1533358.53      6820686.53      1533497.21      6820834.58
      1533456.35      6820898.41      1533455.00      6821038.00

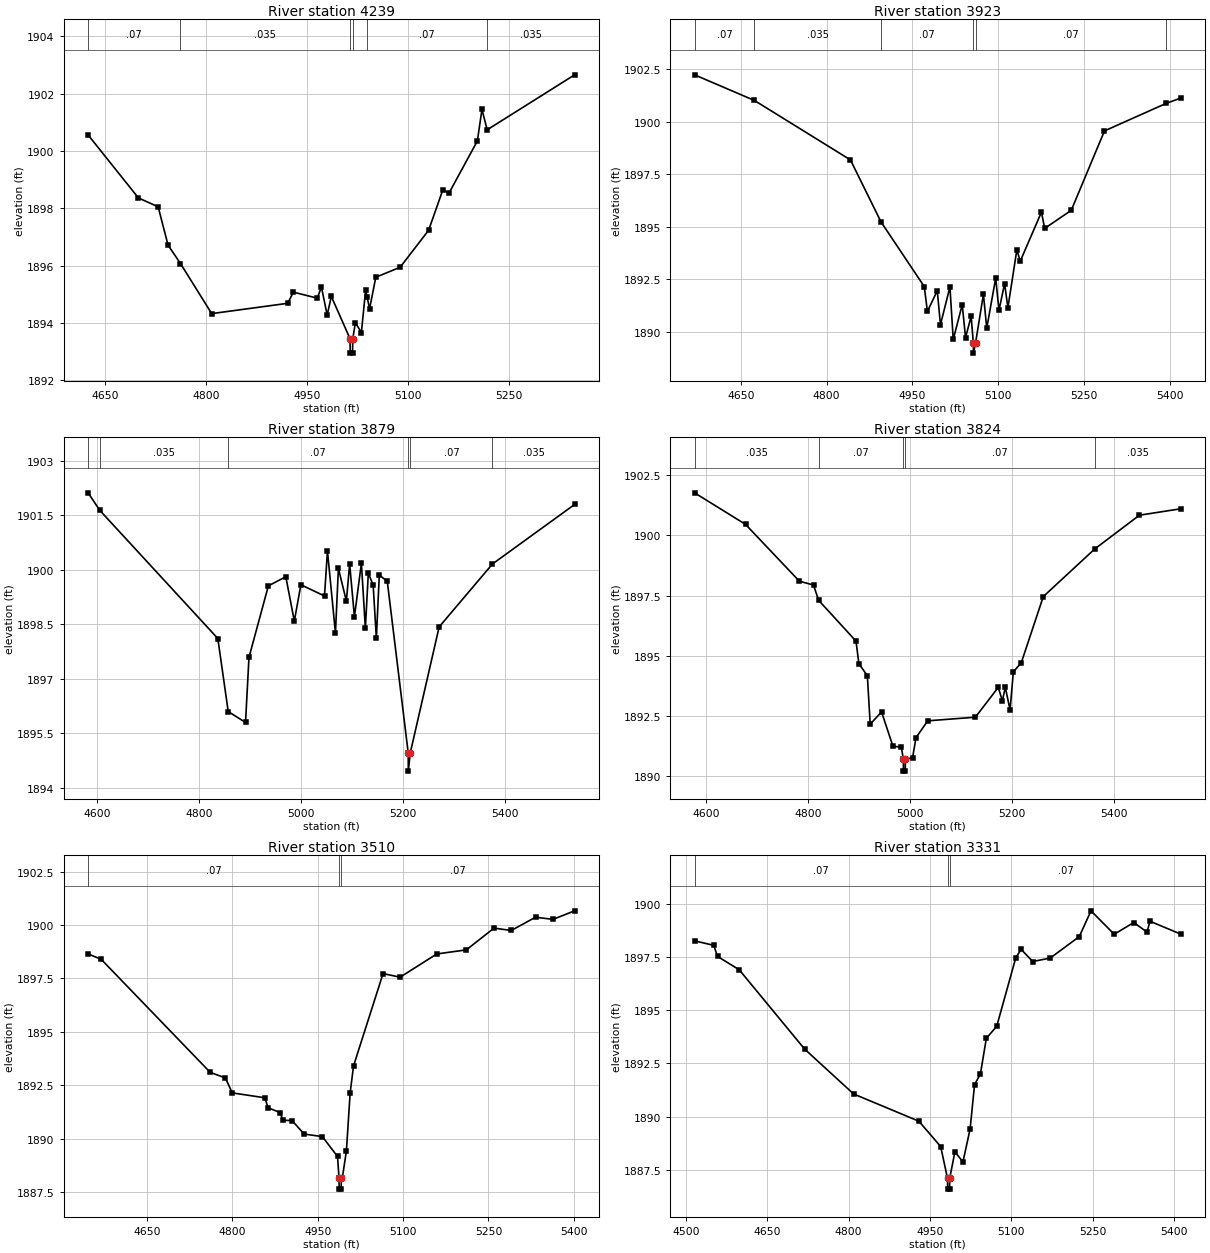
Type RM Length L Ch R = 1,4239,316,316,316
BEGIN DESCRIPTION:
Elm 01 28 4239.238
END DESCRIPTION:
XS GIS Cut Line= 3
      1532896.86      6817905.05      1533199.65      6817683.15
      1533490.31      6817493.79
#Sta/Elev= 30
  4624.6 1900.56  4699.3 1898.36  4728.6 1898.05  4743.3 1896.71  4761.7 1896.07
  4808.1 1894.32  4920.9 1894.68  4929.3 1895.07  4964.8 1894.86  4971.0 1895.25
  4979.5 1894.27  4985.7 1894.92  5013.5 1893.44  5013.7 1892.94  5017.2 1892.94
  5017.5 1893.44  5021.4 1894.00  5030.3 1893.66  5036.6 1895.14  5038.9 1894.89
  5042.5 1894.49  5051.7 1895.59  5087.9 1895.94  5130.1 1897.23  5151.2 1898.64
  5160.4 1898.53  5202.5 1900.35  5209.3 1901.45  5217.1 1900.74  5346.9 1902.66
#Mann=6,-1,0
  4624.6    0.07       0  4761.7   0.035       0  5013.5   0.035       0
  5017.5   0.035       0  5038.9    0.07       0  5217.1   0.035       0
Bank Sta=5013.5,5017.5
Exp/Cntr=0.3,0.1

Type RM Length L Ch R = 1,3923,44,44,44
BEGIN DESCRIPTION:
Elm 01 28 4046.511
END DESCRIPTION:
XS GIS Cut Line= 3
      1532868.17      6818114.39      1533267.86      6817927.01
      1533620.42      6817718.77
#Sta/Elev= 30
  4569.1 1902.23  4673.7 1901.01  4841.7 1898.18  4895.1 1895.23  4970.8 1892.15
  4976.3 1890.97  4993.6 1891.95  4999.1 1890.33  5015.7 1892.13  5021.5 1889.63
  5037.2 1891.29  5043.0 1889.72  5052.8 1890.73  5056.6 1889.48  5056.9 1888.98
  5060.6 1889.48  5074.3 1891.78  5080.1 1890.16  5095.7 1892.55  5101.5 1891.02
  5111.3 1892.29  5117.1 1891.14  5132.8 1893.91  5138.6 1893.35  5175.7 1895.69
  5181.5 1894.92  5227.9 1895.78  5286.0 1899.56  5393.9 1900.87  5420.0 1901.13
#Mann=6,-1,0
  4569.1    0.07       0  4673.7   0.035       0  4895.1    0.07       0
  5056.6    0.07       0  5060.6    0.07       0  5393.9   0.035       0
Bank Sta=5056.6,5060.6
Exp/Cntr=0.3,0.1

Type RM Length L Ch R = 1,3879,55,55,55
BEGIN DESCRIPTION:
Elm 01 28 3871.59
END DESCRIPTION:
XS GIS Cut Line= 3
      1532909.11      6818156.45      1533284.14      6817966.33
      1533747.67      6817698.11
#Sta/Elev= 30
  4581.7 1902.12  4604.5 1901.64  4836.6 1898.11  4857.0 1896.10  4891.0 1895.80
  4897.8 1897.59  4935.9 1899.56  4970.2 1899.81  4986.9 1898.59  4999.8 1899.59
  5046.2 1899.28  5052.0 1900.52  5067.7 1898.26  5073.5 1900.04  5089.2 1899.14
  5095.6 1900.16  5105.0 1898.71  5118.7 1900.18  5126.5 1898.39  5132.3 1899.91
  5141.8 1899.58  5148.1 1898.12  5153.9 1899.86  5169.6 1899.68  5210.7 1894.96
  5210.9 1894.46  5214.7 1894.96  5271.5 1898.43  5376.1 1900.16  5537.7 1901.80
#Mann=6,-1,0
  4581.7    0.07       0  4604.5   0.035       0  4857.0    0.07       0
  5210.7    0.07       0  5214.7    0.07       0  5376.1   0.035       0
Bank Sta=5210.7,5214.7
Exp/Cntr=0.3,0.1

Type RM Length L Ch R = 1,3824,314,314,314
BEGIN DESCRIPTION:
Elm 01 28 7.0
END DESCRIPTION:
XS GIS Cut Line= 3
      1532927.32      6818206.55      1533302.35      6818016.43
      1533765.87      6817748.21
#Sta/Elev= 30
  4576.8 1901.77  4676.9 1900.46  4782.7 1898.10  4810.5 1897.94  4820.4 1897.31
  4894.0 1895.61  4899.6 1894.68  4916.3 1894.17  4921.9 1892.16  4944.2 1892.67
  4966.6 1891.24  4983.1 1891.21  4987.0 1890.71  4987.3 1890.21  4990.8 1890.21
  4991.0 1890.71  5005.1 1890.76  5011.9 1891.60  5035.0 1892.30  5128.6 1892.45
  5173.6 1893.69  5181.6 1893.13  5187.4 1893.69  5196.7 1892.75  5203.2 1894.33
  5218.9 1894.72  5262.0 1897.46  5363.2 1899.44  5450.9 1900.84  5532.8 1901.11
#Mann=5,-1,0
  4576.8   0.035       0  4820.4    0.07       0  4987.0    0.07       0
  4991.0    0.07       0  5363.2   0.035       0
Bank Sta=4987,4991
Exp/Cntr=0.3,0.1

Type RM Length L Ch R = 1,3510,179,179,179
BEGIN DESCRIPTION:
Elm 01 28 3510.28
END DESCRIPTION:
XS GIS Cut Line= 3
      1533144.27      6818248.79      1533568.77      6818110.76
      1533915.09      6817894.64
#Sta/Elev= 30
  4546.8 1898.65  4569.7 1898.40  4761.3 1893.10  4788.0 1892.84  4799.9 1892.14
  4857.2 1891.91  4863.0 1891.44  4883.9 1891.22  4889.1 1890.86  4905.1 1890.84
  4926.3 1890.21  4958.3 1890.09  4984.9 1889.16  4987.6 1888.13  4987.8 1887.63
  4991.3 1887.63  4991.6 1888.13  4993.2 1888.13  5000.5 1889.42  5007.1 1892.14
  5013.0 1893.40  5064.9 1897.73  5094.8 1897.56  5159.3 1898.65  5211.2 1898.84
  5259.8 1899.86  5290.2 1899.75  5332.7 1900.37  5363.4 1900.27  5401.4 1900.67
#Mann=3,-1,0
  4546.8    0.07       0  4987.6    0.07       0  4991.6    0.07       0
Bank Sta=4987.6,4991.6
Exp/Cntr=0.3,0.1

Type RM Length L Ch R = 1,3331,197,197,197
BEGIN DESCRIPTION:
Elm 01 28 3331.38
END DESCRIPTION:
XS GIS Cut Line= 3
      1533172.92      6818306.08      1533652.10      6818261.80
      1534040.03      6818110.80
#Sta/Elev= 30
  4515.8 1898.25  4551.1 1898.04  4558.1 1897.52  4598.2 1896.89  4718.7 1893.17
  4809.1 1891.06  4929.6 1889.78  4969.8 1888.59  4982.4 1887.09  4982.7 1886.59
  4986.2 1886.59  4986.4 1887.09  4996.0 1888.34  5010.9 1887.87  5024.1 1889.42
  5032.3 1891.50  5043.1 1892.00  5054.0 1893.67  5073.2 1894.24  5108.4 1897.46
  5118.2 1897.85  5139.6 1897.28  5171.8 1897.44  5225.5 1898.45  5247.1 1899.66
  5289.9 1898.56  5326.0 1899.11  5350.5 1898.66  5355.9 1899.17  5413.3 1898.56
#Mann=3,-1,0
  4515.8    0.07       0  4982.4    0.07       0  4986.4    0.07       0
Bank Sta=4982.4,4986.4
Exp/Cntr=0.3,0.1

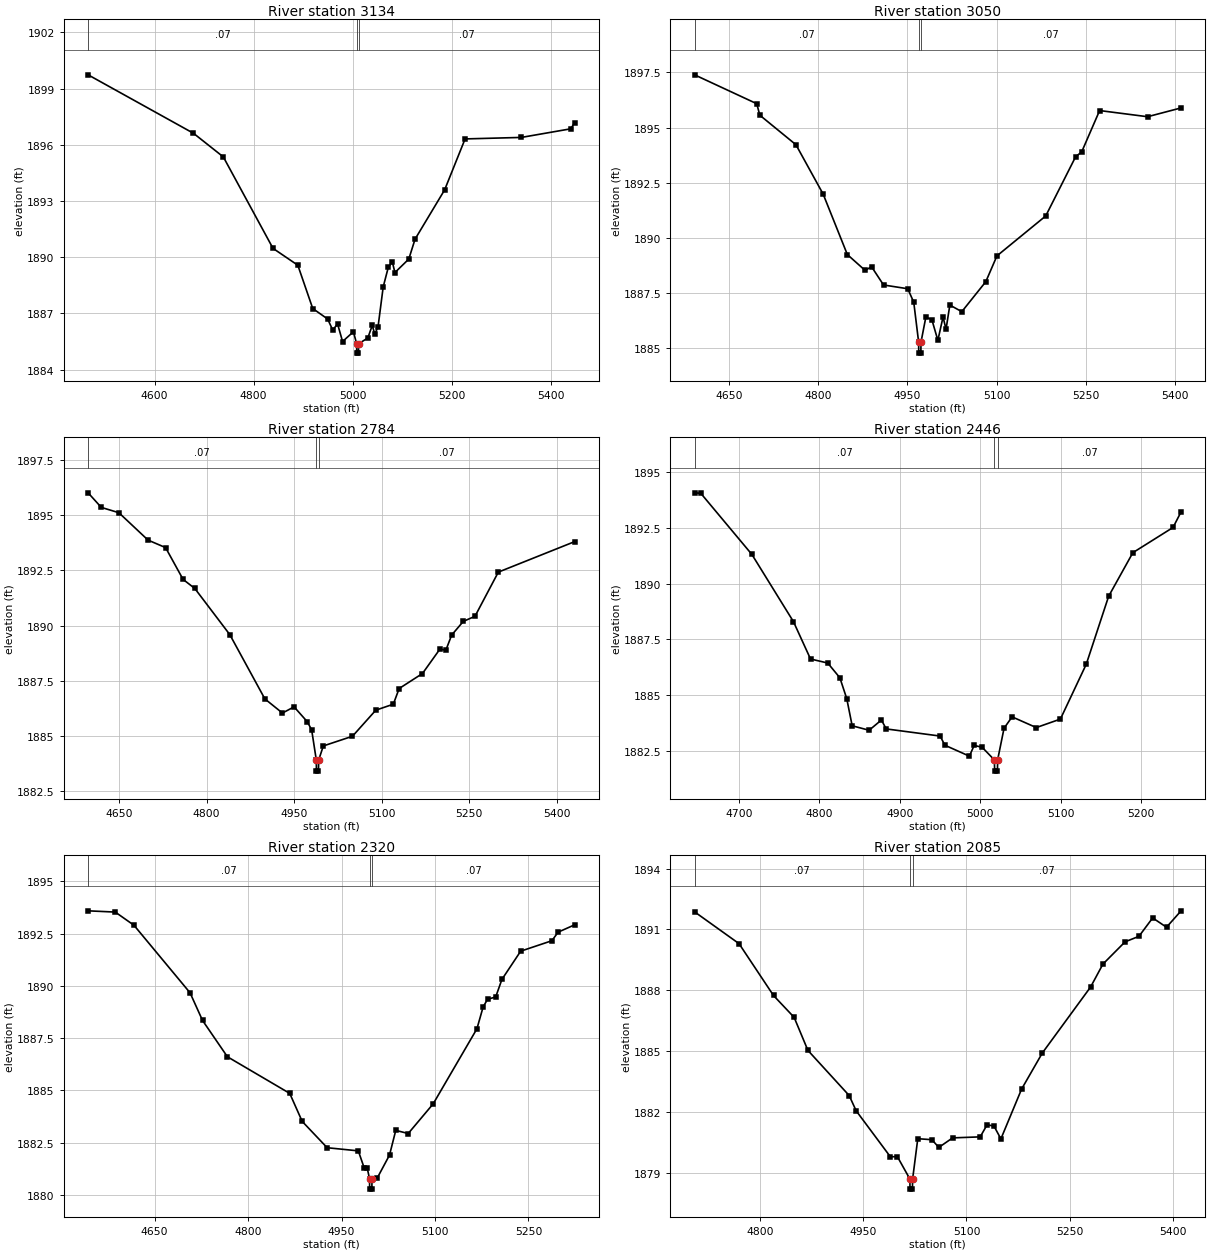
Type RM Length L Ch R = 1,3134,84,84,84
BEGIN DESCRIPTION:
Elm 01 28 3210.24
END DESCRIPTION:
XS GIS Cut Line= 3
      1533132.94      6818475.13      1533666.80      6818433.47
      1534099.05      6818321.50
#Sta/Elev= 30
  4466.0 1899.73  4678.7 1896.61  4738.9 1895.35  4839.2 1890.47  4889.3 1889.57
  4919.4 1887.26  4949.5 1886.70  4959.6 1886.12  4969.6 1886.43  4979.6 1885.50
  5001.5 1886.02  5008.0 1885.38  5008.2 1884.88  5011.7 1884.88  5012.0 1885.38
  5030.6 1885.69  5039.5 1886.36  5044.7 1885.89  5051.3 1886.30  5061.6 1888.41
  5071.9 1889.46  5080.1 1889.74  5085.3 1889.18  5113.3 1889.90  5125.9 1890.96
  5185.6 1893.59  5226.9 1896.31  5340.5 1896.39  5440.3 1896.85  5448.0 1897.18
#Mann=3,-1,0
  4466.0    0.07       0  5008.0    0.07       0  5012.0    0.07       0
Bank Sta=5008,5012
Exp/Cntr=0.3,0.1

Type RM Length L Ch R = 1,3050,266,266,266
BEGIN DESCRIPTION:
Elm 01 28 2992.51
END DESCRIPTION:
XS GIS Cut Line= 3
      1533302.04      6818571.13      1533690.03      6818506.03
      1534110.93      6818459.27
#Sta/Elev= 30
  4592.6 1897.39  4697.0 1896.08  4702.1 1895.56  4762.8 1894.22  4808.5 1891.98
  4849.1 1889.24  4879.0 1888.52  4889.7 1888.69  4909.9 1887.86  4950.5 1887.69
  4960.6 1887.08  4968.8 1885.27  4969.0 1884.77  4972.5 1884.77  4972.8 1885.27
  4980.9 1886.40  4991.0 1886.29  5001.1 1885.35  5009.8 1886.41  5014.8 1885.85
  5021.2 1886.95  5041.3 1886.65  5081.6 1888.01  5100.3 1889.18  5182.2 1890.99
  5232.5 1893.68  5242.5 1893.89  5272.7 1895.77  5353.2 1895.49  5409.5 1895.89
#Mann=3,-1,0
  4592.6    0.07       0  4968.8    0.07       0  4972.8    0.07       0
Bank Sta=4968.8,4972.8
Exp/Cntr=0.3,0.1

Type RM Length L Ch R = 1,2784,338,338,338
BEGIN DESCRIPTION:
Elm 01 28 2707.07
END DESCRIPTION:
XS GIS Cut Line= 3
      1533352.43      6818732.31      1533774.28      6818755.75
      1534185.78      6818755.75
#Sta/Elev= 30
  4597.0 1896.01  4619.6 1895.35  4649.7 1895.11  4699.7 1893.87  4729.8 1893.53
  4759.8 1892.09  4779.9 1891.68  4839.9 1889.59  4900.0 1886.68  4930.1 1886.04
  4950.1 1886.32  4972.6 1885.65  4980.2 1885.28  4988.2 1883.91  4988.4 1883.41
  4991.9 1883.41  4992.2 1883.91  5000.2 1884.55  5050.2 1884.99  5090.2 1886.17
  5120.2 1886.44  5130.2 1887.15  5170.2 1887.83  5200.2 1888.94  5210.2 1888.88
  5220.2 1889.57  5240.2 1890.19  5260.2 1890.42  5300.2 1892.42  5431.0 1893.80
#Mann=3,-1,0
  4597.0    0.07       0  4988.2    0.07       0  4992.2    0.07       0
Bank Sta=4988.2,4992.2
Exp/Cntr=0.3,0.1

Type RM Length L Ch R = 1,2446,126,126,126
BEGIN DESCRIPTION:
Elm 01 28 2445.806
END DESCRIPTION:
XS GIS Cut Line= 3
      1533404.96      6818887.98      1533705.39      6819077.66
      1533954.98      6819088.00
#Sta/Elev= 30
  4644.7 1894.06  4652.4 1894.04  4716.0 1891.30  4767.7 1888.29  4788.9 1886.62
  4810.3 1886.44  4825.4 1885.78  4834.0 1884.84  4840.7 1883.63  4861.8 1883.43
  4877.1 1883.89  4883.0 1883.49  4950.1 1883.17  4956.0 1882.76  4986.5 1882.27
  4992.4 1882.75  5002.3 1882.67  5017.6 1882.10  5017.9 1881.60  5021.4 1881.60
  5021.6 1882.10  5029.6 1883.52  5039.6 1884.03  5069.7 1883.55  5099.7 1883.93
  5131.9 1886.39  5159.7 1889.43  5189.8 1891.38  5239.8 1892.51  5249.8 1893.21
#Mann=3,-1,0
  4644.7    0.07       0  5017.6    0.07       0  5021.6    0.07       0
Bank Sta=5017.6,5021.6
Exp/Cntr=0.3,0.1

Type RM Length L Ch R = 1,2320,235,235,235
BEGIN DESCRIPTION:
Elm 01 28 2320.35
END DESCRIPTION:
XS GIS Cut Line= 3
      1533261.45      6819209.72      1533709.39      6819199.30
      1534041.41      6819222.65
#Sta/Elev= 30
  4543.2 1893.59  4586.8 1893.53  4616.8 1892.90  4706.8 1889.67  4726.8 1888.35
  4766.8 1886.61  4866.8 1884.86  4886.8 1883.52  4926.9 1882.26  4976.9 1882.11
  4986.6 1881.27  4991.3 1881.27  4994.9 1880.78  4995.1 1880.28  4998.6 1880.28
  4998.9 1880.78  5006.9 1880.79  5027.0 1881.91  5037.0 1883.09  5057.0 1882.94
  5097.1 1884.36  5167.3 1887.95  5177.3 1889.00  5184.4 1889.36  5197.4 1889.47
  5207.4 1890.31  5237.5 1891.66  5287.6 1892.16  5297.6 1892.57  5324.1 1892.92
#Mann=3,-1,0
  4543.2    0.07       0  4994.9    0.07       0  4998.9    0.07       0
Bank Sta=4994.9,4998.9
Exp/Cntr=0.3,0.1

Type RM Length L Ch R = 1,2085,215,215,215
BEGIN DESCRIPTION:
Elm 01 28 2084.64
END DESCRIPTION:
XS GIS Cut Line= 3
      1533360.40      6819355.55      1533649.50      6819365.97
      1534066.14      6819334.72
#Sta/Elev= 30
  4704.8 1891.87  4769.4 1890.30  4819.5 1887.74  4849.5 1886.66  4869.5 1885.03
  4929.5 1882.80  4939.6 1882.05  4989.3 1879.78  4999.6 1879.78  5017.7 1878.68
  5017.9 1878.18  5021.4 1878.18  5021.7 1878.68  5029.2 1880.67  5049.7 1880.62
  5059.8 1880.24  5079.8 1880.71  5119.9 1880.76  5130.0 1881.36  5140.0 1881.29
  5150.0 1880.66  5180.1 1883.12  5210.2 1884.90  5280.4 1888.16  5298.3 1889.29
  5330.5 1890.39  5350.6 1890.66  5370.6 1891.57  5390.7 1891.11  5411.9 1891.92
#Mann=3,-1,0
  4704.8    0.07       0  5017.7    0.07       0  5021.7    0.07       0
Bank Sta=5017.7,5021.7
Exp/Cntr=0.3,0.1

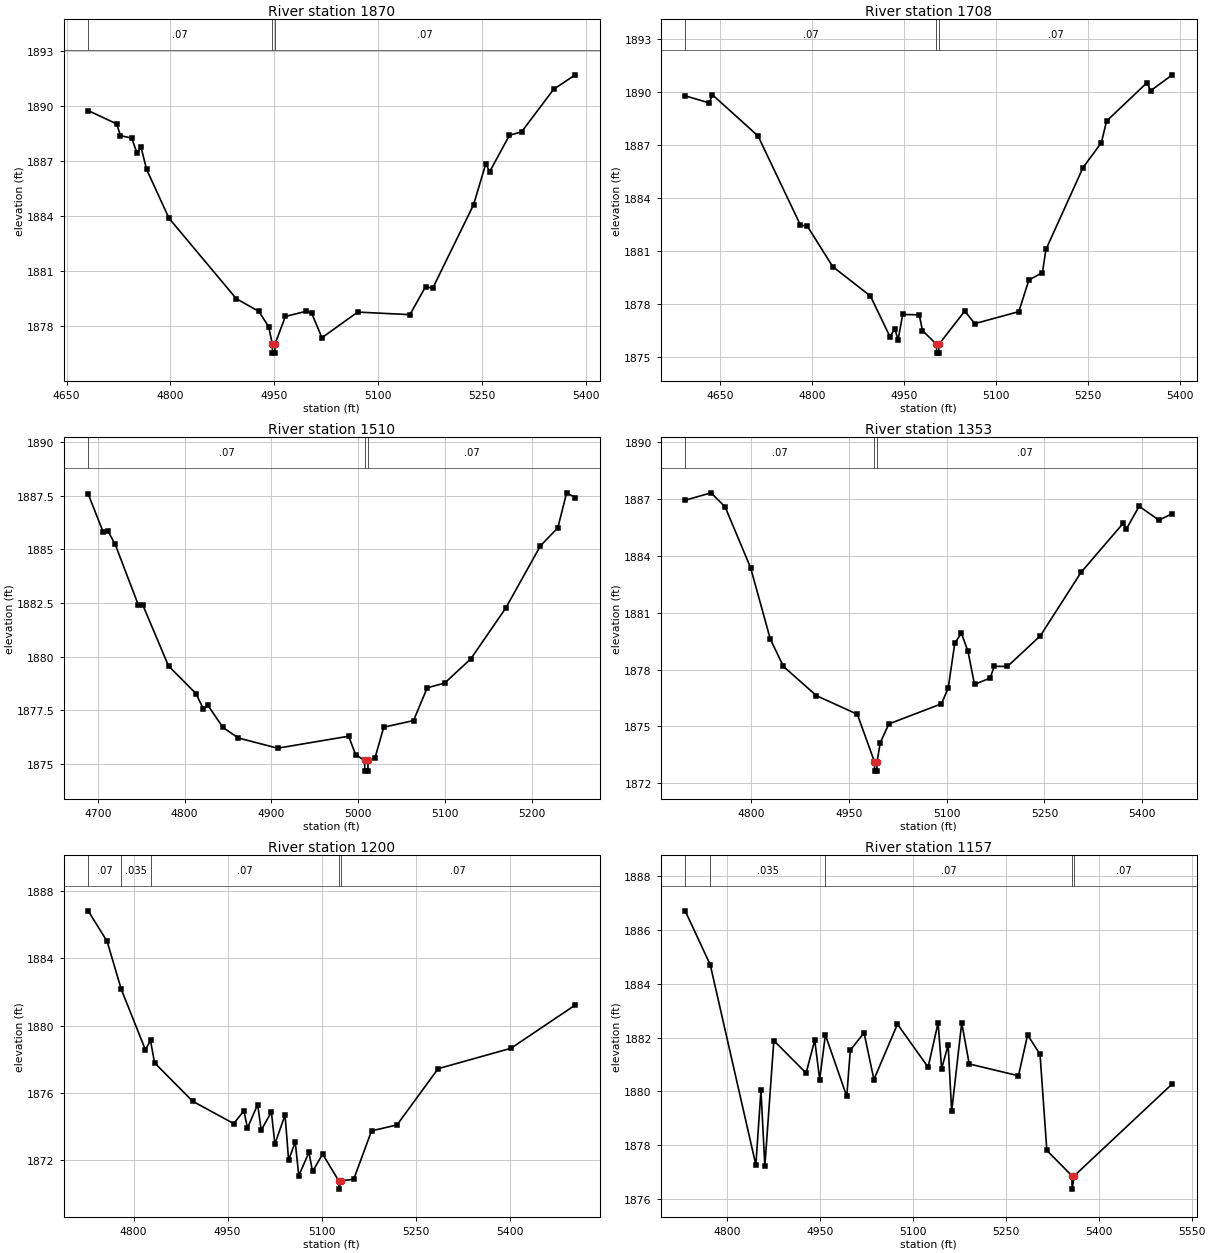
Type RM Length L Ch R = 1,1870,162,162,162
BEGIN DESCRIPTION:
Elm 01 28 1869.57
END DESCRIPTION:
XS GIS Cut Line= 3
      1533456.83      6819670.64      1533751.06      6819550.87
      1534102.66      6819392.00
#Sta/Elev= 30
  4681.1 1889.77  4722.3 1889.04  4727.8 1888.40  4743.9 1888.27  4751.9 1887.43
  4757.3 1887.79  4765.5 1886.56  4797.9 1883.89  4895.1 1879.50  4927.5 1878.81
  4941.9 1877.97  4947.0 1877.03  4947.3 1876.53  4950.8 1876.53  4951.0 1877.03
  4965.9 1878.53  4995.4 1878.81  5003.7 1878.73  5018.7 1877.37  5070.4 1878.77
  5145.8 1878.63  5168.4 1880.16  5178.7 1880.07  5237.7 1884.63  5255.4 1886.87
  5260.9 1886.43  5289.5 1888.42  5307.1 1888.61  5353.3 1890.93  5384.6 1891.72
#Mann=3,-1,0
  4681.1    0.07       0  4947.0    0.07       0  4951.0    0.07       0
Bank Sta=4947,4951
Exp/Cntr=0.3,0.1

Type RM Length L Ch R = 1,1708,198,198,198
BEGIN DESCRIPTION:
Elm 01 28 1708.03
END DESCRIPTION:
XS GIS Cut Line= 3
      1533422.91      6819803.48      1533805.75      6819699.30
      1534157.33      6819514.40
#Sta/Elev= 30
  4593.5 1889.77  4632.7 1889.37  4637.9 1889.83  4712.2 1887.50  4781.4 1882.45
  4792.6 1882.39  4834.0 1880.10  4895.5 1878.43  4927.3 1876.13  4935.3 1876.58
  4940.5 1875.94  4948.0 1877.39  4975.1 1877.37  4980.2 1876.48  5003.1 1875.70
  5003.3 1875.20  5006.8 1875.20  5007.1 1875.70  5049.2 1877.58  5065.6 1876.87
  5137.3 1877.55  5153.7 1879.34  5175.8 1879.76  5181.5 1881.07  5241.9 1885.70
  5271.9 1887.12  5280.3 1888.34  5346.4 1890.52  5352.1 1890.06  5387.5 1890.96
#Mann=3,-1,0
  4593.5    0.07       0  5003.1    0.07       0  5007.1    0.07       0
Bank Sta=5003.1,5007.1
Exp/Cntr=0.3,0.1

Type RM Length L Ch R = 1,1510,157,157,157
BEGIN DESCRIPTION:
Elm 01 28 1510.03
END DESCRIPTION:
XS GIS Cut Line= 3
      1533604.96      6819938.01      1533905.61      6819858.04
      1534155.00      6819838.00
#Sta/Elev= 30
  4688.9 1887.59  4706.4 1885.79  4711.6 1885.86  4720.0 1885.24  4746.6 1882.42
  4751.7 1882.42  4781.5 1879.56  4813.1 1878.27  4821.7 1877.55  4826.9 1877.72
  4844.2 1876.69  4861.8 1876.20  4907.2 1875.72  4989.0 1876.28  4997.1 1875.42
  5007.4 1875.15  5007.7 1874.65  5011.2 1874.65  5011.4 1875.15  5019.5 1875.28
  5029.5 1876.70  5063.8 1877.01  5079.6 1878.54  5099.7 1878.76  5129.8 1879.89
  5169.9 1882.25  5210.1 1885.17  5230.1 1886.01  5240.2 1887.64  5250.2 1887.42
#Mann=3,-1,0
  4688.9    0.07       0  5007.4    0.07       0  5011.4    0.07       0
Bank Sta=5007.4,5011.4
Exp/Cntr=0.3,0.1

Type RM Length L Ch R = 1,1353,153,153,153
BEGIN DESCRIPTION:
Elm 01 28 1353.496
END DESCRIPTION:
XS GIS Cut Line= 3
      1533555.71      6819954.51      1533853.82      6819998.91
      1534295.37      6820063.89
#Sta/Elev= 30
  4698.6 1886.93  4738.3 1887.32  4759.9 1886.58  4799.0 1883.37  4829.3 1879.60
  4849.5 1878.16  4900.1 1876.62  4962.8 1875.64  4989.1 1873.14  4989.3 1872.64
  4992.8 1872.64  4993.1 1873.14  4998.1 1874.15  5011.3 1875.13  5091.9 1876.19
  5102.3 1877.02  5112.4 1879.38  5122.5 1879.92  5132.6 1878.97  5142.7 1877.21
  5166.7 1877.55  5173.0 1878.17  5193.2 1878.16  5243.8 1879.78  5306.1 1883.12
  5370.8 1885.71  5375.9 1885.42  5395.4 1886.61  5425.7 1885.88  5446.3 1886.22
#Mann=3,-1,0
  4698.6    0.07       0  4989.1    0.07       0  4993.1    0.07       0
Bank Sta=4989.1,4993.1
Exp/Cntr=0.3,0.1

Type RM Length L Ch R = 1,1200,43,43,43
BEGIN DESCRIPTION:
Elm 01 28 4.0
END DESCRIPTION:
XS GIS Cut Line= 5
      1533606.99      6819967.95      1533737.41      6820021.04
      1533886.34      6820295.95      1533990.26      6820284.23
      1534196.11      6820357.64
#Sta/Elev= 30
  4727.7 1886.81  4757.9 1885.00  4780.5 1882.15  4819.0 1878.56  4827.1 1879.12
  4833.5 1877.79  4894.2 1875.51  4959.8 1874.18  4976.0 1874.94  4981.7 1873.92
  4997.9 1875.31  5003.6 1873.79  5019.8 1874.87  5025.4 1872.97  5041.6 1874.69
  5047.3 1872.01  5057.8 1873.09  5063.5 1871.09  5079.7 1872.47  5085.4 1871.34
  5101.5 1872.37  5127.1 1870.79  5127.4 1870.29  5131.1 1870.79  5151.0 1870.87
  5179.5 1873.75  5220.1 1874.10  5285.6 1877.44  5401.7 1878.65  5504.3 1881.22
#Mann=5,-1,0
  4727.7    0.07       0  4780.5   0.035       0  4827.1    0.07       0
  5127.1    0.07       0  5131.1    0.07       0
Bank Sta=5127.1,5131.1
Exp/Cntr=0.3,0.1

Type RM Length L Ch R = 1,1157,51,51,51
BEGIN DESCRIPTION:
Elm 01 28 1153.496
END DESCRIPTION:
XS GIS Cut Line= 5
      1533597.40      6819975.33      1533717.20      6820066.49
      1533866.13      6820341.40      1533970.05      6820329.68
      1534175.78      6820403.05
#Sta/Elev= 30
  4732.6 1886.72  4773.1 1884.71  4846.7 1877.26  4854.9 1880.04  4861.2 1877.22
  4875.7 1881.89  4927.8 1880.68  4941.7 1881.91  4949.7 1880.44  4958.9 1882.10
  4993.4 1879.81  4999.1 1881.53  5021.3 1882.18  5037.2 1880.44  5075.2 1882.50
  5124.7 1880.90  5140.8 1882.55  5146.5 1880.84  5157.0 1881.73  5162.7 1879.25
  5178.9 1882.55  5191.0 1881.02  5270.5 1880.58  5285.2 1882.10  5305.3 1881.38
  5316.3 1877.80  5356.7 1876.86  5357.0 1876.36  5360.7 1876.86  5518.8 1880.28
#Mann=5,-1,0
  4732.6    0.07       0  4773.1   0.035       0  4958.9    0.07       0
  5356.7    0.07       0  5360.7    0.07       0
Bank Sta=5356.7,5360.7
Exp/Cntr=0.3,0.1

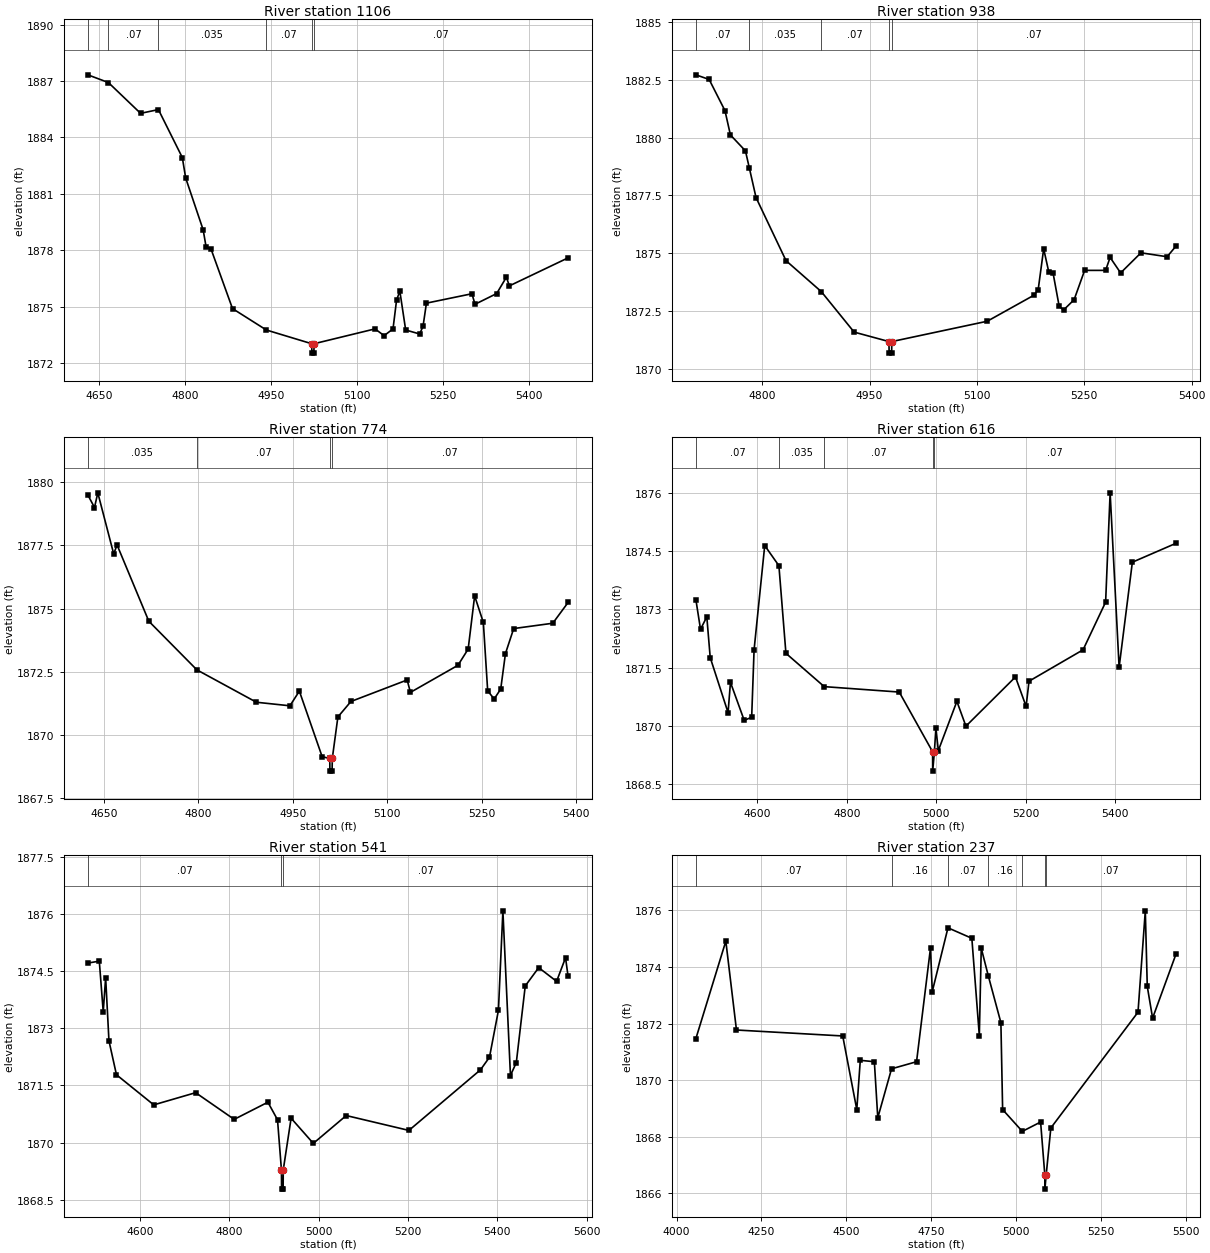
Type RM Length L Ch R = 1,1106,168,168,168
BEGIN DESCRIPTION:
Elm 01 28 2.0
END DESCRIPTION:
XS GIS Cut Line= 4
      1533481.63      6819953.96      1533658.68      6820066.65
      1533839.53      6820388.58      1534081.35      6820481.26
#Sta/Elev= 30
  4630.7 1887.33  4666.6 1886.92  4722.8 1885.28  4753.9 1885.48  4795.6 1882.93
  4801.5 1881.84  4832.0 1879.08  4837.2 1878.16  4845.6 1878.07  4883.2 1874.89
  4942.3 1873.75  5021.5 1873.02  5021.7 1872.52  5025.2 1872.52  5025.5 1873.02
  5131.9 1873.81  5147.8 1873.45  5163.3 1873.81  5169.5 1875.34  5175.2 1875.82
  5185.4 1873.75  5209.8 1873.54  5215.7 1873.95  5221.6 1875.18  5301.0 1875.68
  5306.4 1875.12  5344.2 1875.69  5361.1 1876.56  5366.4 1876.10  5468.8 1877.59
#Mann=6,-1,0
  4630.7   0.035       0  4666.6    0.07       0  4753.9   0.035       0
  4942.3    0.07       0  5021.5    0.07       0  5025.5    0.07       0
Bank Sta=5021.5,5025.5
Exp/Cntr=0.3,0.1

Type RM Length L Ch R = 1,938,164,164,164
BEGIN DESCRIPTION:
Elm 01 28 937.988
END DESCRIPTION:
XS GIS Cut Line= 3
      1533451.56      6820084.70      1533618.63      6820324.79
      1533924.79      6820547.18
#Sta/Elev= 30
  4707.5 1882.72  4726.0 1882.52  4748.1 1881.17  4755.7 1880.12  4776.7 1879.43
  4782.0 1878.71  4791.5 1877.41  4833.4 1874.68  4882.7 1873.34  4928.5 1871.59
  4977.2 1871.18  4977.4 1870.68  4980.9 1870.68  4981.2 1871.18  5114.5 1872.06
  5179.4 1873.18  5185.6 1873.42  5193.3 1875.19  5200.3 1874.21  5206.5 1874.13
  5215.0 1872.70  5221.2 1872.55  5235.8 1872.99  5250.5 1874.26  5279.8 1874.26
  5286.1 1874.82  5300.8 1874.15  5329.2 1875.02  5365.7 1874.85  5378.4 1875.32
#Mann=5,-1,0
  4707.5    0.07       0  4782.0   0.035       0  4882.7    0.07       0
  4977.2    0.07       0  4981.2    0.07       0
Bank Sta=4977.2,4981.2
Exp/Cntr=0.3,0.1

Type RM Length L Ch R = 1,774,158,158,158
BEGIN DESCRIPTION:
Elm 01 28 773.743
END DESCRIPTION:
XS GIS Cut Line= 3
      1533405.14      6820106.43      1533533.89      6820459.06
      1533908.51      6820557.72
#Sta/Elev= 30
  4624.6 1879.49  4635.2 1878.99  4640.5 1879.57  4665.7 1877.16  4671.1 1877.51
  4721.5 1874.50  4797.8 1872.58  4892.4 1871.30  4945.6 1871.16  4960.6 1871.74
  4996.8 1869.15  5008.9 1869.08  5009.1 1868.58  5012.6 1868.58  5012.9 1869.08
  5021.8 1870.72  5042.5 1871.33  5131.8 1872.18  5137.0 1871.69  5212.5 1872.76
  5228.7 1873.40  5239.0 1875.50  5252.8 1874.45  5259.7 1871.75  5270.0 1871.43
  5280.4 1871.82  5287.9 1873.22  5301.0 1874.21  5363.1 1874.42  5387.4 1875.24
#Mann=4,-1,0
  4624.6   0.035       0  4797.8    0.07       0  5008.9    0.07       0
  5012.9    0.07       0
Bank Sta=5008.9,5012.9
Exp/Cntr=0.3,0.1

Type RM Length L Ch R = 1,616,75,75,75
BEGIN DESCRIPTION:
Elm 01 28 604.38
END DESCRIPTION:
XS GIS Cut Line= 3
      1533181.34      6820008.50      1533397.46      6820520.67
      1533911.61      6820584.55
#Sta/Elev= 30
  4462.6 1873.25  4472.9 1872.49  4487.0 1872.81  4494.6 1871.76  4534.5 1870.34
  4539.9 1871.12  4570.6 1870.14  4587.3 1870.22  4592.7 1871.96  4616.5 1874.65
  4648.2 1874.13  4663.9 1871.87  4749.6 1871.01  4917.3 1870.87  4991.9 1869.33
  4992.1 1868.83  4995.9 1869.33  4999.3 1869.94  5004.7 1869.36  5046.2 1870.63
  5066.4 1869.99  5177.2 1871.26  5201.0 1870.50  5207.5 1871.15  5328.4 1871.96
  5378.8 1873.19  5388.9 1876.01  5409.0 1871.51  5438.6 1874.22  5536.6 1874.71
#Mann=5,-1,0
  4462.6    0.07       0  4648.2   0.035       0  4749.6    0.07       0
  4991.9    0.07       0  4995.9    0.07       0
Bank Sta=4991.9,4995.9
Exp/Cntr=0.3,0.1

Type RM Length L Ch R = 1,541,304,304,304
BEGIN DESCRIPTION:
Elm 01 28 544.123
END DESCRIPTION:
XS GIS Cut Line= 4
      1533125.92      6820124.13      1533293.68      6820542.71
      1533376.26      6820573.88      1533910.66      6820598.95
#Sta/Elev= 30
  4483.9 1874.71  4509.6 1874.76  4518.4 1873.43  4523.8 1874.33  4531.2 1872.67
  4548.0 1871.78  4631.4 1870.99  4725.1 1871.31  4811.3 1870.61  4886.7 1871.06
  4908.2 1870.60  4917.0 1869.28  4917.3 1868.78  4920.8 1868.78  4921.0 1869.28
  4938.6 1870.64  4988.3 1869.98  5061.9 1870.71  5202.1 1870.32  5362.2 1871.91
  5382.3 1872.24  5402.3 1873.47  5412.3 1876.08  5429.2 1871.76  5442.3 1872.10
  5462.3 1874.11  5492.4 1874.59  5532.4 1874.23  5552.4 1874.85  5558.1 1874.36
#Mann=3,-1,0
  4483.9    0.07       0  4917.0    0.07       0  4921.0    0.07       0
Bank Sta=4917,4921
Exp/Cntr=0.3,0.1

Type RM Length L Ch R = 1,237,102,102,102
BEGIN DESCRIPTION:
Elm 01 28 1.0
END DESCRIPTION:
XS GIS Cut Line= 6
      1533099.78      6820053.50      1533217.72      6820451.40
      1533303.34      6820772.36      1533407.04      6820826.48
      1533552.54      6820811.62      1533901.27      6820608.88
#Sta/Elev= 30
  4057.1 1871.47  4145.2 1874.91  4176.5 1871.77  4489.3 1871.56  4530.7 1868.96
  4541.0 1870.70  4582.4 1870.65  4592.5 1868.67  4633.0 1870.40  4706.6 1870.65
  4747.7 1874.67  4752.9 1873.13  4799.1 1875.38  4869.4 1875.01  4891.4 1871.57
  4897.1 1874.66  4917.9 1873.68  4954.9 1872.03  4960.0 1868.96  5018.0 1868.19
  5071.8 1868.52  5084.2 1866.65  5084.4 1866.15  5088.2 1866.65  5101.9 1868.31
  5358.5 1872.40  5380.0 1875.98  5385.8 1873.31  5401.5 1872.19  5470.9 1874.47
#Mann=7,-1,0
  4057.1    0.07       0  4633.0    0.16       0  4799.1    0.07       0
  4917.9    0.16       0  5018.0    0.07       0  5084.2    0.07       0
  5088.2    0.07       0
Bank Sta=5084.2,5088.2
Exp/Cntr=0.3,0.1

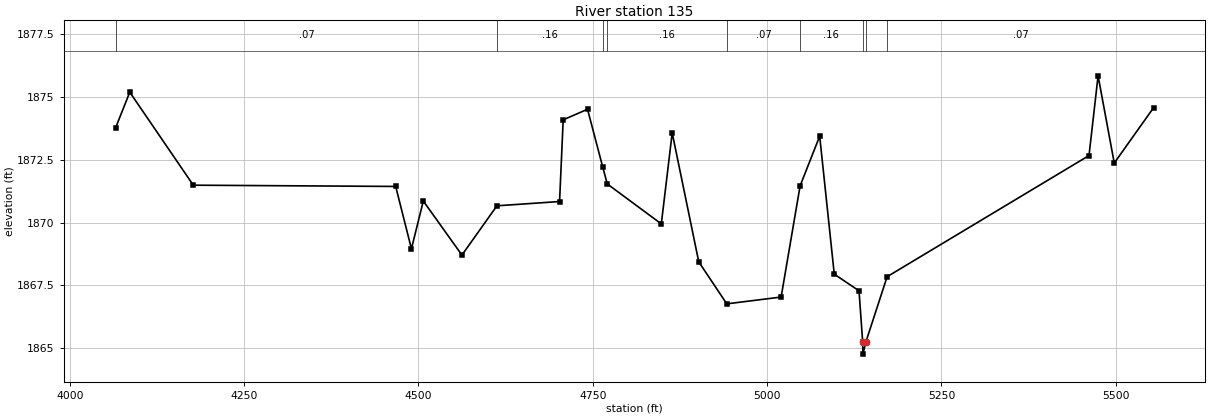
Type RM Length L Ch R = 1,135,0,0,0
BEGIN DESCRIPTION:
Elm 01 28 241.597
END DESCRIPTION:
XS GIS Cut Line= 5
      1533094.94      6820101.32      1533212.88      6820499.22
      1533304.63      6820843.47      1533502.52      6820920.72
      1533909.65      6820622.80
#Sta/Elev= 30
  4065.9 1873.78  4086.1 1875.19  4177.2 1871.49  4467.4 1871.44  4490.0 1868.96
  4507.0 1870.86  4562.4 1868.71  4612.6 1870.67  4702.4 1870.84  4707.6 1874.09
  4742.5 1874.51  4764.3 1872.21  4770.8 1871.54  4848.3 1869.95  4863.9 1873.57
  4902.0 1868.44  4942.2 1866.77  5020.1 1867.04  5047.3 1871.46  5075.4 1873.44
  5096.3 1867.95  5131.8 1867.29  5137.0 1865.27  5137.4 1864.77  5141.8 1865.27
  5172.1 1867.85  5461.6 1872.67  5474.6 1875.84  5497.8 1872.37  5554.1 1874.57
#Mann=9,-1,0
  4065.9    0.07       0  4612.6    0.16       0  4764.3    0.07       0
  4770.8    0.16       0  4942.2    0.07       0  5047.3    0.16       0
  5137.0    0.07       0  5141.8    0.16       0  5172.1    0.07       0
Bank Sta=5137,5141.8
Exp/Cntr=0.3,0.1

Chan Stop Cuts=-1