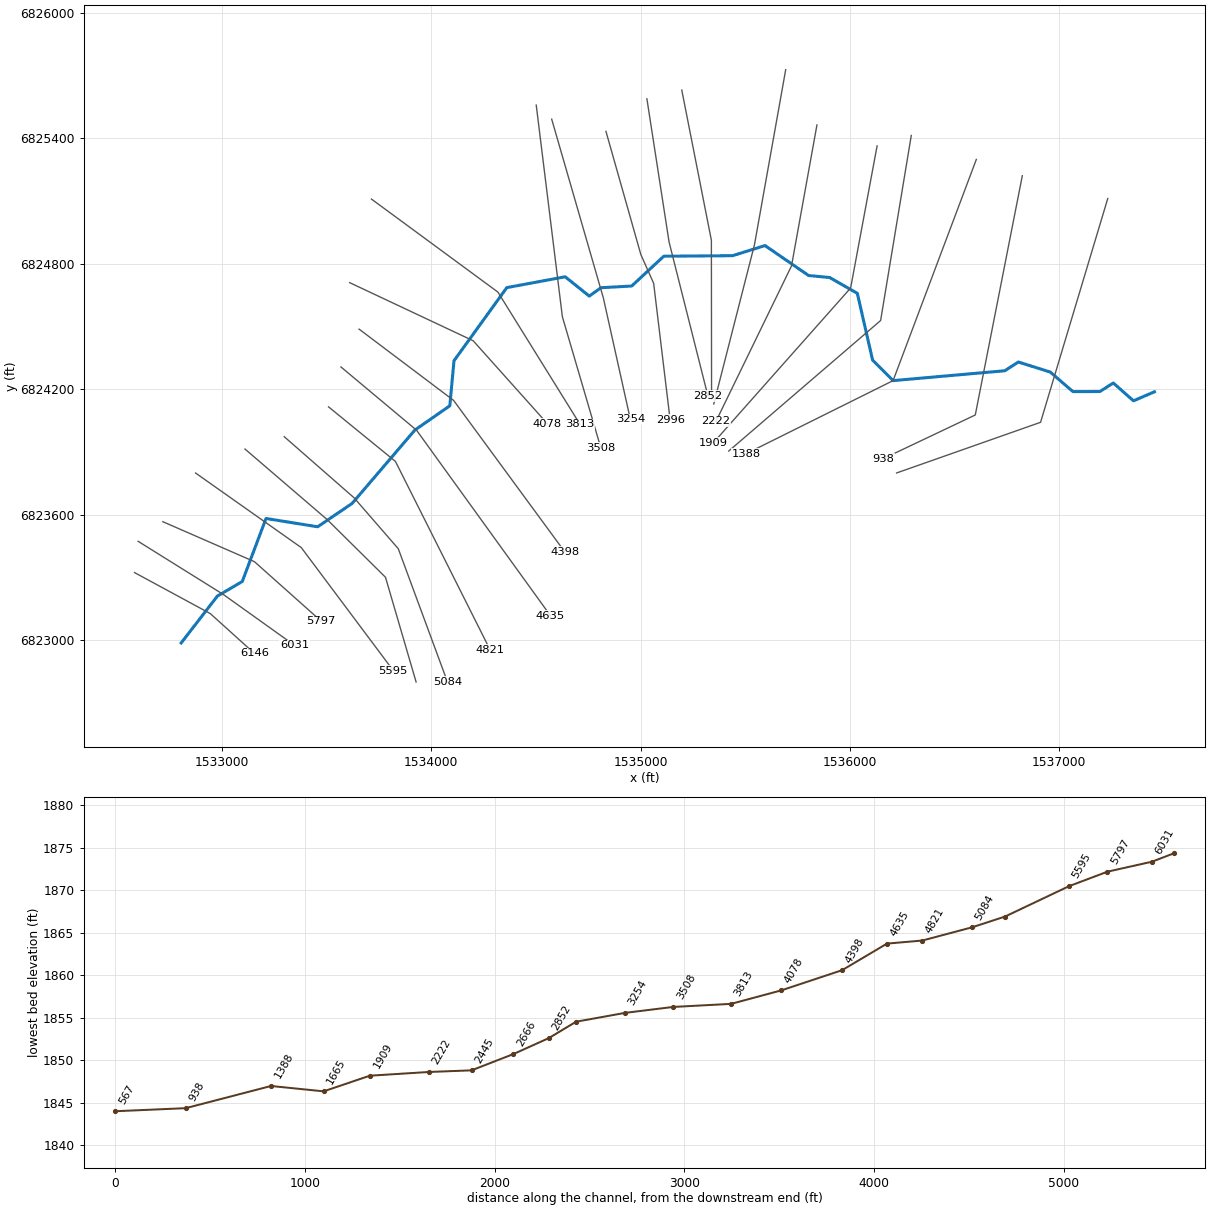
--- Elm 01 29.prj (project) ---

Proj Title=Elm 01 29 Base Level Engineering
Current Plan=p01
Default Exp/Contr=0.3,0.1
English Units
Geom File=g01
Flow File=f01
Plan File=p01
BEGIN DESCRIPTION:
Elm 01 29
END DESCRIPTION:

--- Elm 01 29.p01 (plan) ---

Plan Title=Multiple Run
Short Identifier=Multiple
Geom File=g01
Flow File=f01
Subcritical Flow
K Sum by GR= 0
Std Step Tol= 0.01
Critical Tol= 0.01
Num of Std Step Trials= 20
Max Error Tol= 0.3
Flow Tol Ratio= 0.001
Split Flow NTrial= 30
Split Flow Tol= 0.02
Split Flow Ratio= 0.02
Log Output Level= 0
Friction Slope Method= 1
Unsteady Friction Slope Method= 2
Unsteady Bridges Friction Slope Method= 1
Parabolic Critical Depth
Global Vel Dist=  1 , 1 , 1
Global Log Level= 0
CheckData=True
Encroach Param= -1, 0, 0, 0
BEGIN DESCRIPTION:
Multiple Run
END DESCRIPTION:

--- Elm 01 29.f01 (steady flow) ---

Flow Title=Multiple
Number of Profiles=7
Profile Names=10-year,25-year,50-year,1pct_min,100-year,1pct_plu,500-year
River Rch & RM= Elm 01 29,Reach-1,6146
     214     296     363     277     443     610     669
River Rch & RM= Elm 01 29,Reach-1,2852
     351     499     624     483     775    1070    1210
Boundary for River Rch & Prof#=Elm 01 29,Reach-1,1
Up Type=0
Dn Type=3
Dn Slope=0.005
Boundary for River Rch & Prof#=Elm 01 29,Reach-1,2
Up Type=0
Dn Type=3
Dn Slope=0.005
Boundary for River Rch & Prof#=Elm 01 29,Reach-1,3
Up Type=0
Dn Type=3
Dn Slope=0.005
Boundary for River Rch & Prof#=Elm 01 29,Reach-1,4
Up Type=0
Dn Type=3
Dn Slope=0.005
Boundary for River Rch & Prof#=Elm 01 29,Reach-1,5
Up Type=0
Dn Type=3
Dn Slope=0.005
Boundary for River Rch & Prof#=Elm 01 29,Reach-1,6
Up Type=0
Dn Type=3
Dn Slope=0.005
Boundary for River Rch & Prof#=Elm 01 29,Reach-1,7
Up Type=0
Dn Type=3
Dn Slope=0.005

--- Elm 01 29.g01 (geometry) ---

Geom Title=Existing Conditions

River Reach=Elm 01 29,Reach-1
Reach XY= 30
      1532805.00      6822988.00      1532977.87      6823211.83
      1533096.98      6823281.66      1533210.41      6823582.84
      1533457.29      6823543.10      1533621.67      6823654.65
      1533921.42      6824005.08      1534088.58      6824121.20
      1534108.55      6824336.53      1534360.85      6824685.94
      1534639.78      6824737.75      1534754.90      6824645.33
      1534810.86      6824685.52      1534957.45      6824693.47
      1535110.85      6824835.94      1535439.78      6824838.52
      1535594.47      6824886.92      1535802.64      6824743.76
      1535903.42      6824734.18      1536035.56      6824658.55
      1536108.61      6824339.48      1536206.45      6824241.53
      1536739.84      6824288.66      1536805.00      6824330.44
      1536957.42      6824282.46      1537065.44      6824189.04
      1537194.56      6824189.38      1537258.42      6824230.18
      1537354.93      6824145.07      1537455.00      6824188.00

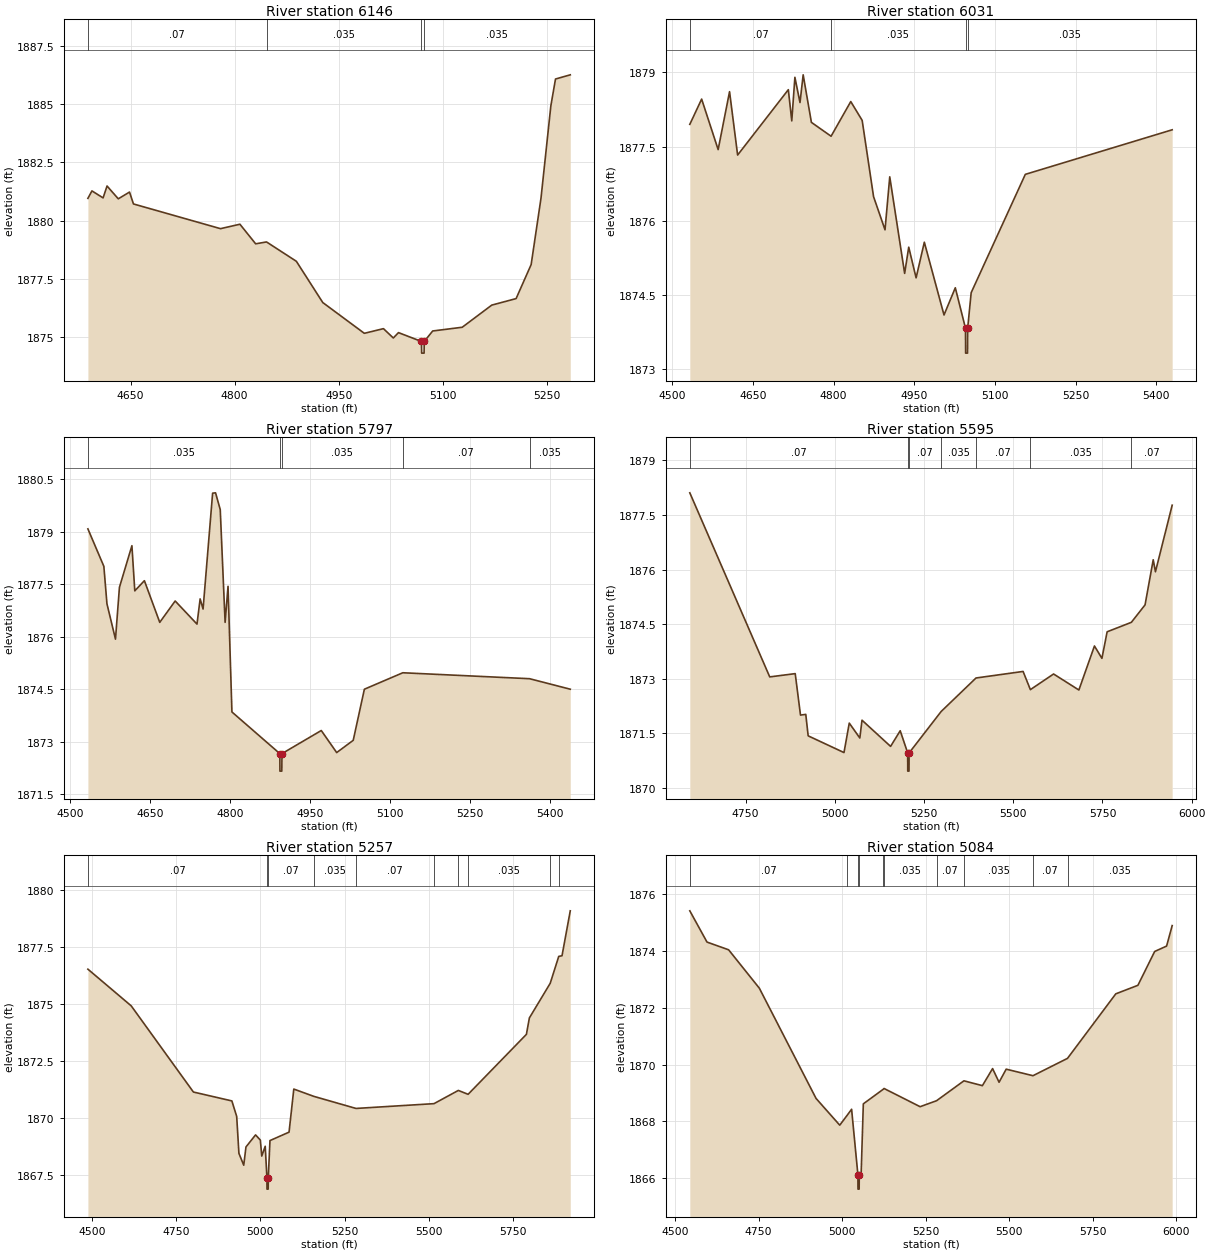
Type RM Length L Ch R = 1,6146,115,115,115
BEGIN DESCRIPTION:
Elm 01 29 6146.321
END DESCRIPTION:
XS GIS Cut Line= 3
      1532582.25      6823324.29      1532944.22      6823128.34
      1533155.00      6822938.00
#Sta/Elev= 30
  4588.4 1880.95  4594.2 1881.27  4610.3 1880.97  4616.0 1881.48  4632.2 1880.93
  4648.4 1881.22  4654.1 1880.71  4779.6 1879.65  4807.6 1879.84  4830.3 1879.00
  4846.0 1879.08  4889.0 1878.25  4927.1 1876.48  4987.0 1875.16  5014.6 1875.36
  5028.8 1874.96  5036.3 1875.19  5069.4 1874.81  5069.7 1874.31  5073.2 1874.31
  5073.4 1874.81  5085.6 1875.26  5128.2 1875.42  5170.8 1876.37  5205.9 1876.65
  5227.6 1878.11  5241.8 1880.96  5256.0 1884.92  5262.7 1886.07  5284.0 1886.25
#Mann=4,-1,0
  4588.4    0.07       0  4846.0   0.035       0  5069.4   0.035       0
  5073.4   0.035       0
Bank Sta=5069.4,5073.4
Exp/Cntr=0.3,0.1

Type RM Length L Ch R = 1,6031,234,234,234
BEGIN DESCRIPTION:
Elm 01 29 6030.72
END DESCRIPTION:
XS GIS Cut Line= 3
      1532599.60      6823473.60      1533005.83      6823220.14
      1533346.12      6822977.08
#Sta/Elev= 30
  4532.5 1877.95  4554.5 1878.46  4585.2 1877.44  4606.4 1878.61  4621.4 1877.33
  4715.7 1878.65  4722.1 1878.02  4727.9 1878.90  4737.4 1878.39  4743.3 1878.95
  4758.6 1877.99  4795.2 1877.71  4831.8 1878.41  4853.0 1878.03  4874.2 1876.49
  4895.5 1875.82  4904.3 1876.89  4932.0 1874.94  4939.6 1875.47  4953.3 1874.85
  4968.6 1875.57  5005.2 1874.10  5026.2 1874.65  5045.2 1873.83  5045.4 1873.33
  5048.9 1873.33  5049.2 1873.83  5055.7 1874.55  5156.4 1876.94  5429.5 1877.84
#Mann=4,-1,0
  4532.5    0.07       0  4795.2   0.035       0  5045.2   0.035       0
  5049.2   0.035       0
Bank Sta=5045.2,5049.2
Exp/Cntr=0.3,0.1

Type RM Length L Ch R = 1,5797,202,202,202
BEGIN DESCRIPTION:
Elm 01 29 5797.26
END DESCRIPTION:
XS GIS Cut Line= 3
      1532717.59      6823567.38      1533155.14      6823376.39
      1533473.81      6823092.35
#Sta/Elev= 30
  4533.2 1879.08  4563.1 1878.01  4568.9 1876.94  4584.9 1875.93  4592.3 1877.41
  4615.7 1878.60  4621.1 1877.31  4639.1 1877.60  4667.9 1876.41  4696.8 1877.02
  4737.7 1876.36  4743.6 1877.08  4749.1 1876.79  4767.0 1880.10  4772.5 1880.11
  4781.3 1879.63  4790.4 1876.41  4795.9 1877.44  4803.2 1873.85  4893.0 1872.66
  4893.2 1872.16  4896.7 1872.16  4897.0 1872.66  4970.7 1873.32  4999.6 1872.69
  5030.6 1873.04  5051.5 1874.50  5123.6 1874.97  5361.2 1874.80  5437.5 1874.50
#Mann=5,-1,0
  4533.2   0.035       0  4893.0   0.035       0  4897.0   0.035       0
  5123.6    0.07       0  5361.2   0.035       0
Bank Sta=4893,4897
Exp/Cntr=0.3,0.1

Type RM Length L Ch R = 1,5595,338,338,338
BEGIN DESCRIPTION:
Elm 01 29 5594.69
END DESCRIPTION:
XS GIS Cut Line= 3
      1532873.93      6823799.97      1533378.97      6823443.67
      1533818.48      6822856.03
#Sta/Elev= 30
  4593.5 1878.11  4817.5 1873.05  4888.9 1873.14  4903.7 1872.00  4918.5 1872.02
  4925.2 1871.43  5025.6 1870.97  5040.4 1871.78  5070.0 1871.37  5076.1 1871.86
  5156.2 1871.14  5183.2 1871.57  5204.1 1870.96  5204.3 1870.46  5207.8 1870.46
  5208.1 1870.96  5298.0 1872.10  5395.6 1873.02  5527.6 1873.20  5548.0 1872.70
  5613.0 1873.13  5683.9 1872.69  5727.6 1873.90  5748.5 1873.56  5763.1 1874.29
  5831.0 1874.55  5869.4 1875.03  5892.3 1876.27  5898.5 1875.94  5945.4 1877.77
#Mann=7,-1,0
  4593.5    0.07       0  5204.1    0.07       0  5208.1    0.07       0
  5298.0   0.035       0  5395.6    0.07       0  5548.0   0.035       0
  5831.0    0.07       0
Bank Sta=5204.1,5208.1
Exp/Cntr=0.3,0.1

Type RM Length L Ch R = 1,5257,173,173,173
BEGIN DESCRIPTION:
Elm 01 29 5257.47
END DESCRIPTION:
XS GIS Cut Line= 4
      1533109.98      6823914.60      1533502.36      6823577.78
      1533781.28      6823301.89      1533927.50      6822801.54
#Sta/Elev= 30
  4488.7 1876.53  4617.2 1874.92  4801.6 1871.14  4915.7 1870.75  4930.0 1870.07
  4936.6 1868.45  4950.9 1867.93  4957.5 1868.73  4986.0 1869.26  5000.2 1869.03
  5004.3 1868.33  5014.6 1868.76  5019.7 1867.38  5019.9 1866.88  5023.4 1866.88
  5023.7 1867.38  5028.7 1869.01  5085.3 1869.38  5099.4 1871.27  5158.7 1870.95
  5283.9 1870.42  5515.2 1870.63  5587.4 1871.21  5616.4 1871.04  5789.3 1873.67
  5798.1 1874.39  5859.9 1875.91  5885.2 1877.09  5894.9 1877.12  5919.4 1879.09
#Mann=10,-1,0
  4488.7    0.07       0  5019.7    0.07       0  5023.7    0.07       0
  5158.7   0.035       0  5283.9    0.07       0  5515.2   0.035       0
  5587.4    0.07       0  5616.4   0.035       0  5859.9    0.07       0
  5885.2   0.035       0
Bank Sta=5019.7,5023.7
Exp/Cntr=0.3,0.1

Type RM Length L Ch R = 1,5084,263,263,263
BEGIN DESCRIPTION:
Elm 01 29 5083.96
END DESCRIPTION:
XS GIS Cut Line= 4
      1533297.46      6823973.64      1533630.83      6823681.94
      1533842.42      6823438.30      1534077.40      6822801.75
#Sta/Elev= 30
  4544.2 1875.41  4595.7 1874.31  4660.3 1874.04  4752.3 1872.69  4922.2 1868.81
  4993.1 1867.87  5016.1 1868.23  5028.6 1868.43  5047.5 1866.12  5047.7 1865.62
  5051.2 1865.62  5051.5 1866.12  5057.1 1866.14  5063.7 1868.62  5123.0 1869.13
  5125.8 1869.16  5233.7 1868.52  5283.0 1868.73  5364.9 1869.43  5420.2 1869.26
  5450.7 1869.86  5470.1 1869.38  5491.4 1869.84  5571.6 1869.61  5675.0 1870.22
  5819.6 1872.49  5885.8 1872.79  5936.0 1873.98  5971.7 1874.17  5988.4 1874.89
#Mann=10,-1,0
  4544.2    0.07       0  5016.1   0.035       0  5047.5    0.07       0
  5051.5   0.035       0  5123.0    0.07       0  5125.8   0.035       0
  5283.0    0.07       0  5364.9   0.035       0  5571.6    0.07       0
  5675.0   0.035       0
Bank Sta=5047.5,5051.5
Exp/Cntr=0.3,0.1

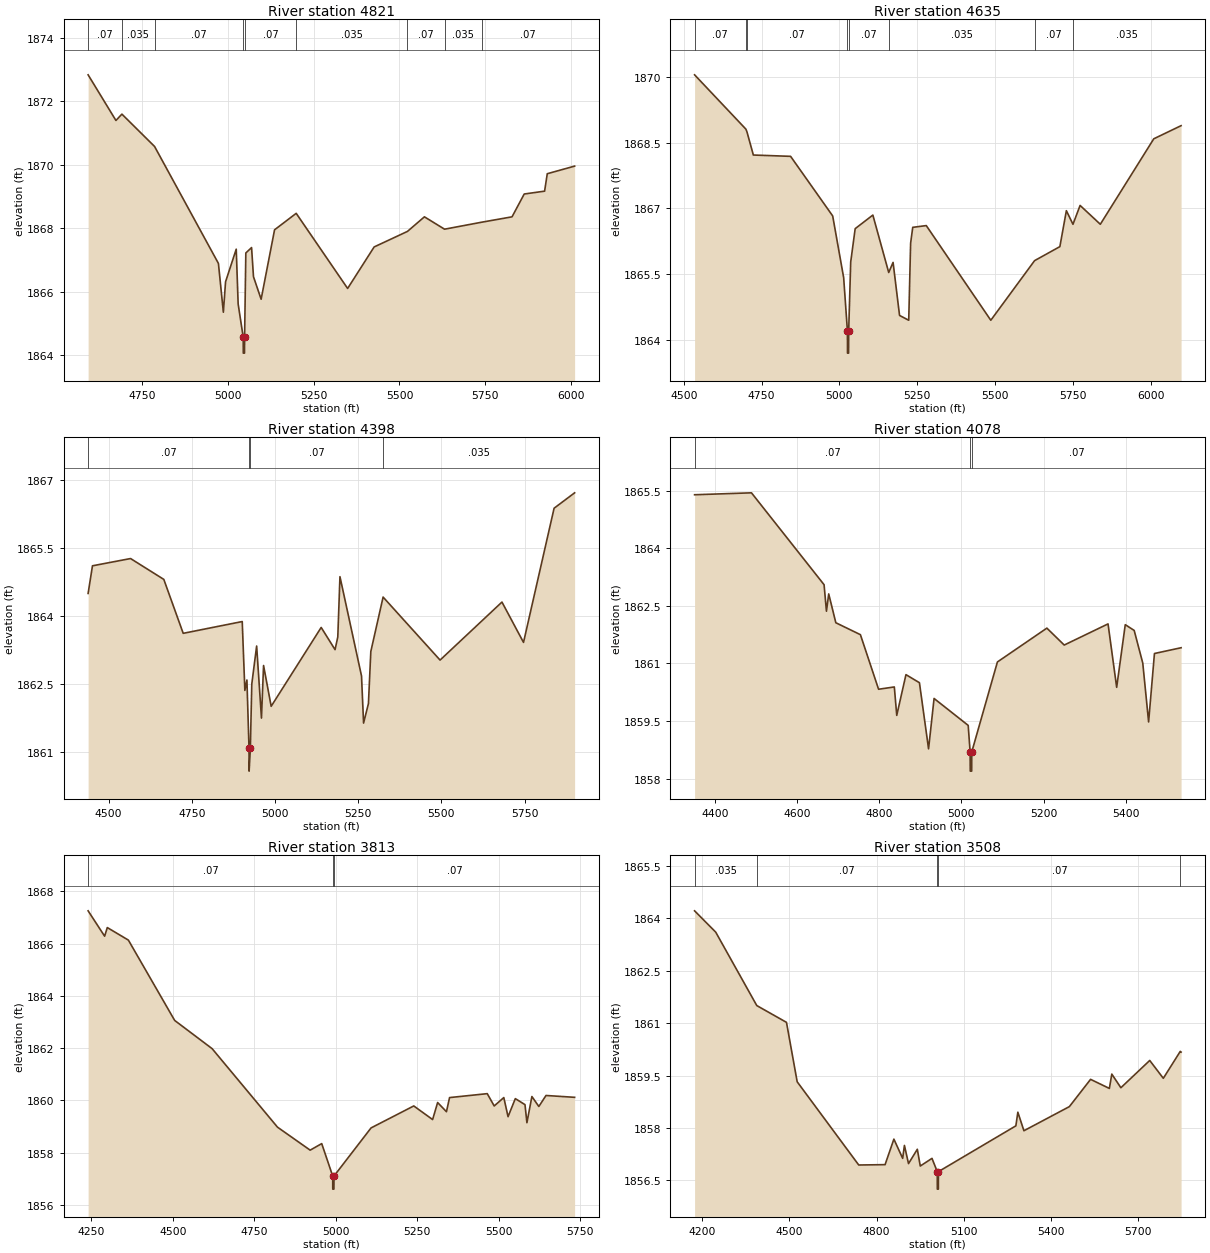
Type RM Length L Ch R = 1,4821,186,186,186
BEGIN DESCRIPTION:
Elm 01 29 4820.82
END DESCRIPTION:
XS GIS Cut Line= 3
      1533509.28      6824115.99      1533828.75      6823855.55
      1534280.25      6822956.76
#Sta/Elev= 30
  4592.5 1872.84  4673.6 1871.40  4691.0 1871.60  4786.2 1870.58  4972.3 1866.89
  4986.7 1865.35  4993.1 1866.31  5024.2 1867.34  5029.8 1865.61  5044.6 1864.56
  5044.8 1864.06  5048.3 1864.06  5048.6 1864.56  5052.2 1867.22  5068.9 1867.39
  5074.5 1866.47  5096.8 1865.76  5135.9 1867.95  5199.0 1868.47  5348.9 1866.10
  5426.2 1867.41  5523.3 1867.90  5572.7 1868.36  5631.4 1867.97  5739.5 1868.19
  5828.1 1868.36  5863.6 1869.08  5923.0 1869.17  5930.8 1869.72  6010.5 1869.96
#Mann=9,-1,0
  4592.5    0.07       0  4691.0   0.035       0  4786.2    0.07       0
  5044.6    0.07       0  5048.6    0.07       0  5199.0   0.035       0
  5523.3    0.07       0  5631.4   0.035       0  5739.5    0.07       0
Bank Sta=5044.6,5048.6
Exp/Cntr=0.3,0.1

Type RM Length L Ch R = 1,4635,237,237,237
BEGIN DESCRIPTION:
Elm 01 29 4634.64
END DESCRIPTION:
XS GIS Cut Line= 3
      1533568.37      6824306.91      1533929.44      6824004.86
      1534569.15      6823118.68
#Sta/Elev= 30
  4534.6 1870.05  4699.6 1868.81  4703.3 1868.74  4723.5 1868.22  4843.2 1868.19
  4978.5 1866.83  5013.8 1865.42  5025.9 1864.20  5026.1 1863.70  5029.6 1863.70
  5029.9 1864.20  5036.4 1865.78  5050.8 1866.54  5107.6 1866.85  5158.6 1865.54
  5172.6 1865.77  5193.4 1864.56  5222.9 1864.45  5229.0 1866.21  5235.8 1866.57
  5279.3 1866.61  5486.7 1864.45  5627.4 1865.81  5708.7 1866.13  5729.6 1866.95
  5750.8 1866.64  5773.7 1867.07  5838.7 1866.64  6010.5 1868.59  6098.3 1868.89
#Mann=8,-1,0
  4534.6    0.07       0  4699.6   0.035       0  4703.3    0.07       0
  5025.9    0.07       0  5029.9    0.07       0  5158.6   0.035       0
  5627.4    0.07       0  5750.8   0.035       0
Bank Sta=5025.9,5029.9
Exp/Cntr=0.3,0.1

Type RM Length L Ch R = 1,4398,320,320,320
BEGIN DESCRIPTION:
Elm 01 29 4397.52
END DESCRIPTION:
XS GIS Cut Line= 3
      1533655.11      6824487.52      1534106.53      6824147.22
      1534637.20      6823424.18
#Sta/Elev= 30
  4438.4 1864.49  4451.5 1865.10  4566.0 1865.26  4665.9 1864.80  4724.2 1863.61
  4901.6 1863.87  4909.5 1862.35  4915.7 1862.58  4922.0 1861.07  4922.3 1860.57
  4926.0 1861.07  4930.3 1862.49  4944.9 1863.33  4959.4 1861.74  4965.7 1862.90
  4988.6 1862.00  5138.9 1863.74  5180.6 1863.25  5188.8 1863.53  5195.3 1864.86
  5260.1 1862.67  5266.3 1861.63  5280.9 1862.06  5288.1 1863.21  5325.0 1864.41
  5496.2 1863.02  5682.2 1864.30  5747.0 1863.41  5838.9 1866.37  5900.6 1866.71
#Mann=4,-1,0
  4438.4    0.07       0  4922.0    0.07       0  4926.0    0.07       0
  5325.0   0.035       0
Bank Sta=4922,4926
Exp/Cntr=0.3,0.1

Type RM Length L Ch R = 1,4078,265,265,265
BEGIN DESCRIPTION:
Elm 01 29 4078.38
END DESCRIPTION:
XS GIS Cut Line= 3
      1533610.02      6824709.71      1534200.28      6824431.94
      1534554.45      6824036.11
#Sta/Elev= 30
  4351.0 1865.39  4489.4 1865.44  4666.0 1863.05  4671.8 1862.36  4677.3 1862.81
  4694.6 1862.06  4754.4 1861.75  4798.6 1860.33  4836.9 1860.39  4842.8 1859.65
  4865.2 1860.71  4898.0 1860.50  4920.2 1858.78  4933.6 1860.09  5016.6 1859.39
  5021.3 1858.70  5021.6 1858.20  5025.1 1858.20  5025.3 1858.70  5087.7 1861.04
  5208.0 1861.92  5250.2 1861.48  5356.8 1862.03  5377.8 1860.38  5398.7 1862.01
  5420.4 1861.86  5441.3 1861.01  5455.5 1859.48  5469.7 1861.26  5534.5 1861.41
#Mann=3,-1,0
  4351.0    0.07       0  5021.3    0.07       0  5025.3    0.07       0
Bank Sta=5021.3,5025.3
Exp/Cntr=0.3,0.1

Type RM Length L Ch R = 1,3813,305,305,305
BEGIN DESCRIPTION:
Elm 01 29 3813.31
END DESCRIPTION:
XS GIS Cut Line= 3
      1533714.16      6825109.03      1534318.33      6824664.58
      1534710.23      6824033.39
#Sta/Elev= 30
  4240.4 1867.25  4291.1 1866.28  4299.3 1866.61  4364.0 1866.13  4506.0 1863.06
  4621.0 1861.98  4821.5 1858.98  4921.8 1858.10  4957.3 1858.35  4991.0 1857.11
  4991.2 1856.61  4994.7 1856.61  4995.0 1857.11  5108.7 1858.95  5239.8 1859.79
  5297.6 1859.27  5313.0 1859.92  5340.1 1859.57  5349.6 1860.11  5465.3 1860.26
  5486.6 1859.79  5516.1 1860.11  5529.1 1859.38  5551.4 1860.07  5581.1 1859.84
  5587.0 1859.15  5602.3 1860.15  5623.6 1859.77  5645.6 1860.19  5733.4 1860.12
#Mann=3,-1,0
  4240.4    0.07       0  4991.0    0.07       0  4995.0    0.07       0
Bank Sta=4991,4995
Exp/Cntr=0.3,0.1

Type RM Length L Ch R = 1,3508,254,254,254
BEGIN DESCRIPTION:
Elm 01 29 3507.6
END DESCRIPTION:
XS GIS Cut Line= 3
      1534501.45      6825558.10      1534626.34      6824546.84
      1534810.29      6823919.39
#Sta/Elev= 30
  4174.0 1864.21  4246.7 1863.60  4387.9 1861.50  4490.0 1861.02  4526.8 1859.32
  4738.4 1856.94  4829.0 1856.95  4859.3 1857.68  4889.5 1857.13  4895.5 1857.50
  4909.6 1856.98  4939.9 1857.39  4950.0 1856.91  4990.3 1857.13  5008.4 1856.75
  5008.7 1856.25  5012.2 1856.25  5012.4 1856.75  5278.7 1858.06  5285.5 1858.45
  5306.4 1857.92  5462.7 1858.61  5535.6 1859.39  5600.2 1859.13  5608.6 1859.54
  5639.8 1859.15  5739.0 1859.93  5785.7 1859.42  5844.0 1860.19  5846.8 1860.17
#Mann=5,-1,0
  4174.0   0.035       0  4387.9    0.07       0  5008.4    0.07       0
  5012.4    0.07       0  5844.0   0.035       0
Bank Sta=5008.4,5012.4
Exp/Cntr=0.3,0.1

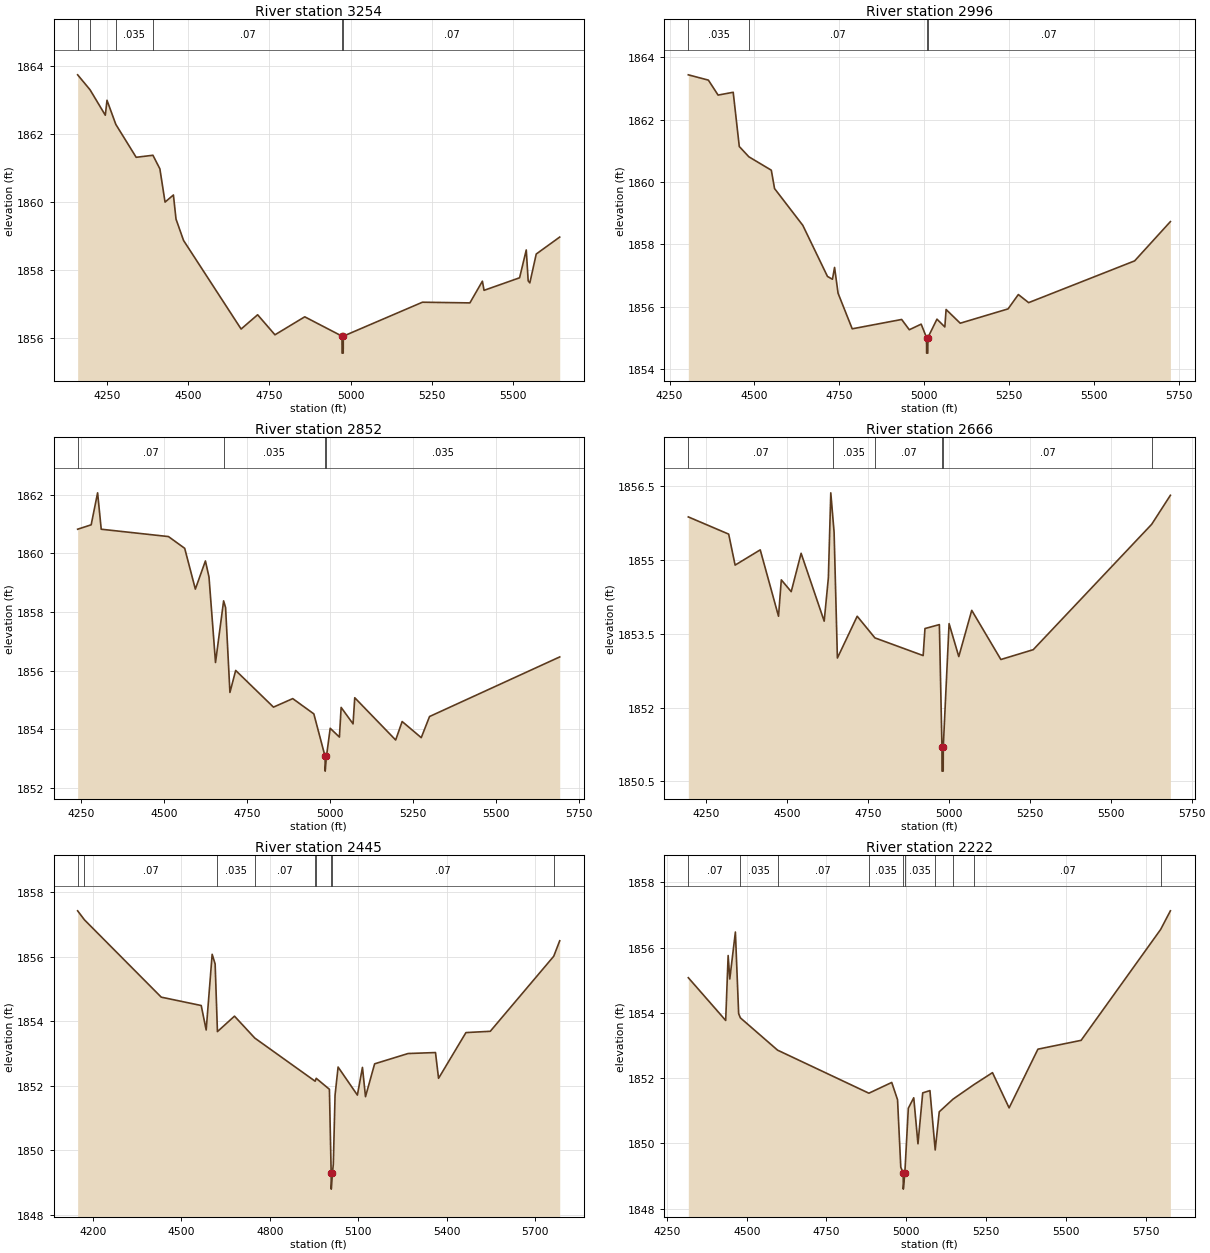
Type RM Length L Ch R = 1,3254,258,258,258
BEGIN DESCRIPTION:
Elm 01 29 3301.12
END DESCRIPTION:
XS GIS Cut Line= 3
      1534575.28      6825490.95      1534822.08      6824636.81
      1534950.88      6824057.53
#Sta/Elev= 30
  4160.2 1863.75  4198.3 1863.31  4245.3 1862.56  4250.5 1863.00  4277.6 1862.29
  4340.2 1861.32  4391.7 1861.38  4413.1 1860.98  4429.0 1860.00  4454.7 1860.21
  4462.7 1859.50  4485.9 1858.87  4662.9 1856.26  4713.7 1856.68  4767.0 1856.09
  4858.6 1856.62  4973.2 1856.05  4973.4 1855.55  4976.9 1855.55  4977.2 1856.05
  5220.5 1857.05  5366.5 1857.03  5404.9 1857.67  5410.0 1857.40  5519.3 1857.77
  5539.8 1858.59  5545.7 1857.68  5550.8 1857.62  5570.5 1858.47  5642.7 1858.97
#Mann=6,-1,0
  4160.2   0.035       0  4198.3    0.07       0  4277.6   0.035       0
  4391.7    0.07       0  4973.2    0.07       0  4977.2    0.07       0
Bank Sta=4973.2,4977.2
Exp/Cntr=0.3,0.1

Type RM Length L Ch R = 1,2996,144,144,144
BEGIN DESCRIPTION:
Elm 01 29 3077.41
END DESCRIPTION:
XS GIS Cut Line= 4
      1534834.60      6825432.40      1535001.20      6824844.16
      1535062.44      6824706.34      1535141.25      6824053.47
#Sta/Elev= 30
  4305.2 1863.44  4364.3 1863.27  4392.9 1862.79  4437.4 1862.88  4455.3 1861.14
  4483.5 1860.81  4549.6 1860.38  4559.2 1859.79  4642.4 1858.61  4715.1 1856.97
  4729.7 1856.88  4735.9 1857.26  4746.3 1856.43  4787.9 1855.29  4933.5 1855.59
  4956.1 1855.26  4991.0 1855.44  5006.8 1855.01  5007.0 1854.51  5010.5 1854.51
  5010.8 1855.01  5037.5 1855.60  5060.7 1855.35  5064.4 1855.91  5106.0 1855.47
  5247.0 1855.93  5277.2 1856.39  5307.5 1856.13  5619.7 1857.47  5725.0 1858.73
#Mann=4,-1,0
  4305.2   0.035       0  4483.5    0.07       0  5006.8    0.07       0
  5010.8    0.07       0
Bank Sta=5006.8,5010.8
Exp/Cntr=0.3,0.1

Type RM Length L Ch R = 1,2852,186,186,186
BEGIN DESCRIPTION:
Elm 01 29 2788.63
END DESCRIPTION:
XS GIS Cut Line= 3
      1535030.14      6825588.18      1535136.16      6824903.75
      1535321.82      6824168.01
#Sta/Elev= 30
  4240.1 1860.82  4280.8 1860.97  4300.2 1862.06  4311.1 1860.82  4513.5 1860.57
  4562.4 1860.17  4594.5 1858.78  4624.8 1859.74  4635.6 1859.19  4655.2 1856.28
  4679.6 1858.38  4685.5 1858.15  4698.6 1855.26  4715.9 1856.01  4829.7 1854.76
  4887.7 1855.05  4951.2 1854.53  4985.1 1853.08  4985.4 1852.58  4989.2 1853.08
  5000.5 1854.04  5028.2 1853.74  5033.4 1854.75  5069.3 1854.19  5074.4 1855.08
  5197.6 1853.64  5217.1 1854.27  5274.6 1853.72  5299.6 1854.44  5691.5 1856.47
#Mann=4,-1,0
  4240.1    0.07       0  4679.6   0.035       0  4985.1   0.035       0
  4989.2   0.035       0
Bank Sta=4985.1,4989.2
Exp/Cntr=0.3,0.1

Type RM Length L Ch R = 1,2666,221,221,221
BEGIN DESCRIPTION:
Elm 01 29 2584.03
END DESCRIPTION:
XS GIS Cut Line= 3
      1535196.80      6825629.90      1535338.29      6824912.07
      1535339.17      6824154.21
#Sta/Elev= 30
  4194.8 1855.88  4319.5 1855.53  4339.4 1854.90  4417.0 1855.21  4473.5 1853.86
  4482.1 1854.60  4512.7 1854.36  4543.3 1855.14  4614.6 1853.76  4627.5 1854.64
  4635.0 1856.37  4640.7 1855.92  4645.2 1855.57  4655.4 1853.01  4716.6 1853.86
  4771.3 1853.42  4920.4 1853.06  4926.0 1853.61  4970.5 1853.69  4978.5 1851.21
  4978.7 1850.71  4982.3 1850.71  4982.6 1851.21  5000.5 1853.71  5030.5 1853.04
  5070.5 1853.98  5160.5 1852.98  5260.5 1853.18  5626.5 1855.73  5684.3 1856.32
#Mann=6,-1,0
  4194.8    0.07       0  4640.7   0.035       0  4771.3    0.07       0
  4978.5    0.07       0  4982.6    0.07       0  5626.5   0.035       0
Bank Sta=4978.5,4982.6
Exp/Cntr=0.3,0.1

Type RM Length L Ch R = 1,2445,223,223,223
BEGIN DESCRIPTION:
Elm 01 29 2445.22
END DESCRIPTION:
XS GIS Cut Line= 3
      1535693.33      6825727.09      1535544.03      6824890.28
      1535349.59      6824129.88
#Sta/Elev= 30
  4148.3 1857.43  4171.4 1857.15  4431.8 1854.75  4567.4 1854.49  4584.2 1853.73
  4604.5 1856.08  4614.6 1855.78  4622.4 1853.68  4680.2 1854.16  4749.0 1853.48
  4953.8 1852.14  4957.4 1852.23  5002.1 1851.89  5008.1 1849.29  5008.4 1848.79
  5012.3 1849.29  5015.4 1849.56  5021.3 1851.71  5031.6 1852.58  5097.0 1851.71
  5114.2 1852.57  5124.5 1851.66  5155.5 1852.68  5269.0 1853.00  5361.9 1853.03
  5372.3 1852.23  5465.2 1853.65  5547.7 1853.69  5762.9 1856.02  5783.2 1856.50
#Mann=9,-1,0
  4148.3    0.16       0  4171.4    0.07       0  4622.4   0.035       0
  4749.0    0.07       0  4953.8   0.035       0  4957.4    0.07       0
  5008.1    0.07       0  5012.3    0.07       0  5762.9   0.035       0
Bank Sta=5008.1,5012.3
Exp/Cntr=0.3,0.1

Type RM Length L Ch R = 1,2222,313,313,313
BEGIN DESCRIPTION:
Elm 01 29 2222.42
END DESCRIPTION:
XS GIS Cut Line= 3
      1535842.64      6825463.20      1535721.11      6824789.58
      1535360.02      6824046.57
#Sta/Elev= 30
  4317.1 1855.08  4434.2 1853.77  4441.9 1855.76  4447.0 1855.04  4464.6 1856.48
  4474.8 1853.98  4480.2 1853.85  4596.7 1852.86  4882.9 1851.54  4954.5 1851.87
  4972.7 1851.34  4982.9 1849.27  4990.4 1849.10  4990.8 1848.60  4995.6 1849.10
  5006.5 1851.08  5023.5 1851.40  5036.7 1849.99  5051.6 1851.55  5074.2 1851.62
  5090.7 1849.80  5103.4 1850.97  5146.8 1851.36  5213.1 1851.81  5270.2 1852.17
  5322.3 1851.09  5412.6 1852.89  5547.9 1853.16  5797.2 1856.56  5827.7 1857.13
#Mann=10,-1,0
  4317.1    0.07       0  4480.2   0.035       0  4596.7    0.07       0
  4882.9   0.035       0  4990.4   0.035       0  4995.6   0.035       0
  5090.7    0.07       0  5146.8   0.035       0  5213.1    0.07       0
  5797.2   0.035       0
Bank Sta=4990.4,4995.6
Exp/Cntr=0.3,0.1

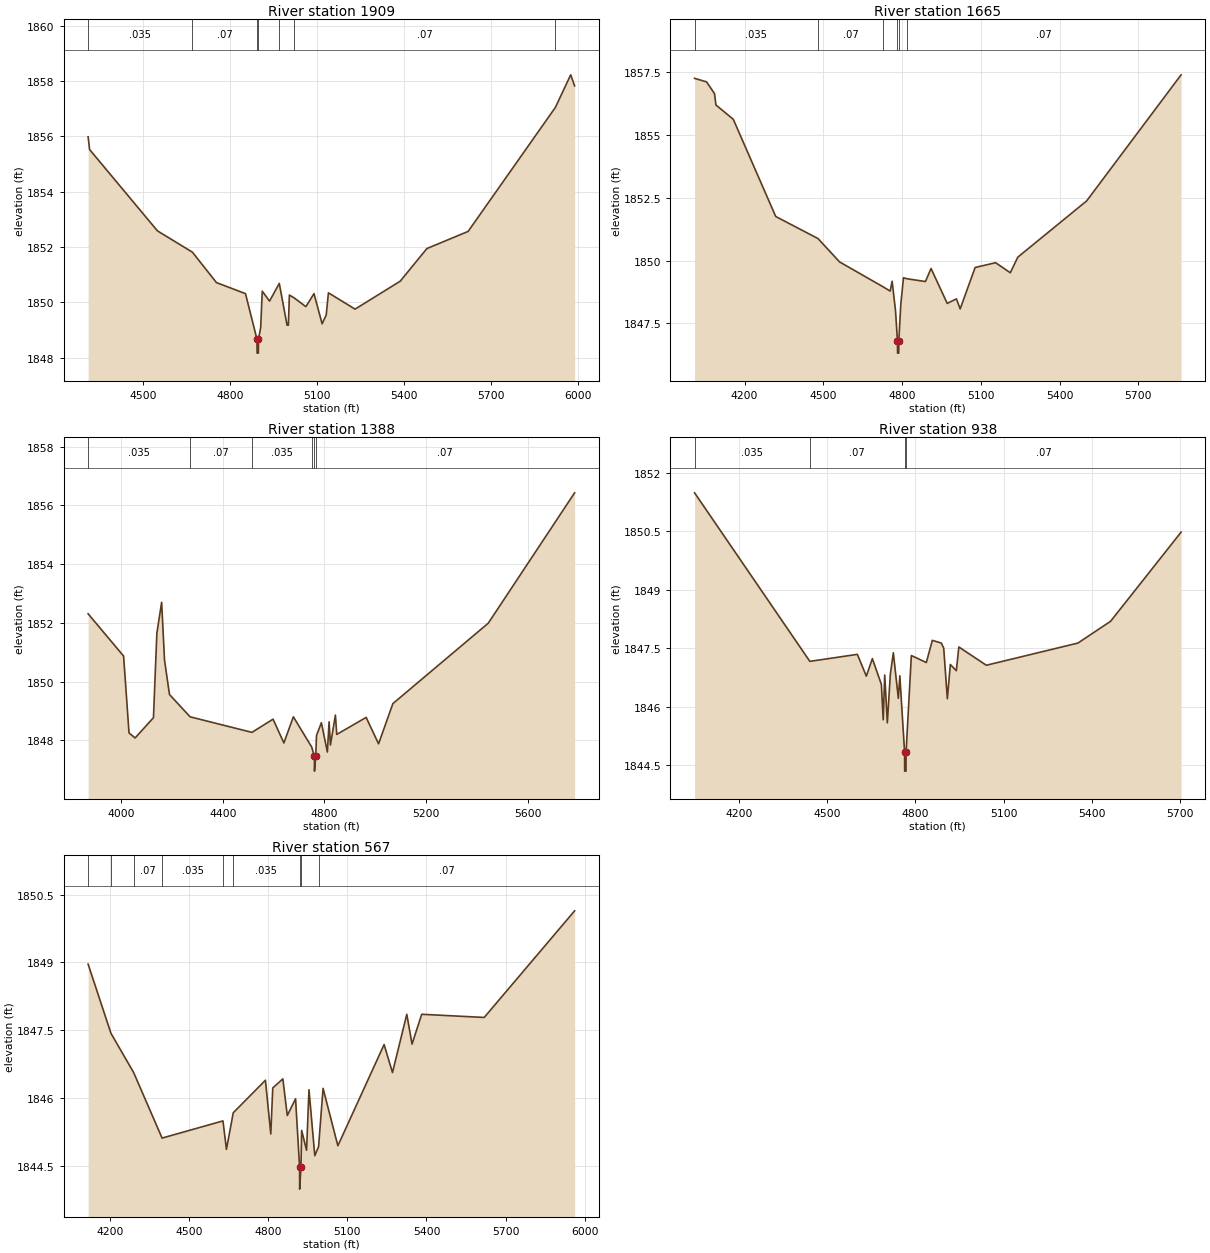
Type RM Length L Ch R = 1,1909,244,244,244
BEGIN DESCRIPTION:
Elm 01 29 1909.029
END DESCRIPTION:
XS GIS Cut Line= 3
      1536130.00      6825362.99      1536003.61      6824684.16
      1535348.73      6823945.58
#Sta/Elev= 30
  4309.5 1855.98  4314.6 1855.52  4548.5 1852.58  4669.1 1851.81  4752.0 1850.71
  4852.2 1850.31  4891.8 1848.66  4892.2 1848.16  4896.6 1848.16  4897.0 1848.66
  4904.5 1849.08  4910.0 1850.40  4935.1 1850.04  4968.7 1850.68  4995.5 1849.17
  5000.0 1849.17  5003.5 1850.26  5020.9 1850.15  5060.4 1849.84  5088.4 1850.31
  5116.4 1849.22  5130.6 1849.54  5138.1 1850.34  5230.1 1849.75  5385.7 1850.76
  5477.7 1851.94  5619.9 1852.56  5920.6 1857.04  5973.6 1858.22  5987.1 1857.82
#Mann=7,-1,0
  4309.5   0.035       0  4669.1    0.07       0  4891.8   0.035       0
  4897.0    0.07       0  4968.7   0.035       0  5020.9    0.07       0
  5920.6   0.035       0
Bank Sta=4891.8,4897
Exp/Cntr=0.3,0.1

Type RM Length L Ch R = 1,1665,277,277,277
BEGIN DESCRIPTION:
Elm 01 29 1671.701
END DESCRIPTION:
XS GIS Cut Line= 3
      1536293.33      6825412.96      1536146.86      6824528.74
      1535421.23      6823905.06
#Sta/Elev= 30
  4009.8 1857.26  4055.4 1857.12  4085.8 1856.65  4091.1 1856.20  4157.2 1855.63
  4318.9 1851.76  4480.1 1850.88  4562.2 1849.95  4726.2 1848.97  4754.8 1848.79
  4762.2 1849.18  4775.0 1848.03  4782.5 1846.82  4782.9 1846.32  4787.4 1846.32
  4787.8 1846.82  4795.3 1848.27  4805.5 1849.32  4819.6 1849.28  4889.2 1849.17
  4910.5 1849.69  4972.1 1848.30  5007.2 1848.48  5021.4 1848.08  5078.5 1849.73
  5156.4 1849.92  5212.4 1849.52  5240.9 1850.14  5503.2 1852.38  5862.9 1857.40
#Mann=6,-1,0
  4009.8   0.035       0  4480.1    0.07       0  4726.2   0.035       0
  4782.5    0.07       0  4787.8   0.035       0  4819.6    0.07       0
Bank Sta=4782.5,4787.8
Exp/Cntr=0.3,0.1

Type RM Length L Ch R = 1,1388,450,450,450
BEGIN DESCRIPTION:
Elm 01 29 1388.499
END DESCRIPTION:
XS GIS Cut Line= 3
      1536604.18      6825298.58      1536206.45      6824241.53
      1535504.65      6823892.50
#Sta/Elev= 30
  3870.6 1852.31  4010.1 1850.87  4031.5 1848.25  4055.5 1848.08  4127.6 1848.77
  4140.9 1851.64  4159.7 1852.70  4171.1 1850.73  4190.6 1849.56  4271.7 1848.80
  4514.9 1848.27  4597.8 1848.72  4640.5 1847.91  4677.7 1848.80  4749.9 1847.77
  4760.4 1847.45  4760.8 1846.95  4765.7 1847.45  4768.7 1848.16  4787.9 1848.60
  4811.5 1847.60  4818.2 1848.63  4823.5 1847.84  4843.1 1848.86  4848.4 1848.20
  4964.0 1848.78  5012.8 1847.88  5069.1 1849.25  5444.3 1851.99  5783.8 1856.43
#Mann=6,-1,0
  3870.6   0.035       0  4271.7    0.07       0  4514.9   0.035       0
  4749.9    0.07       0  4760.4    0.07       0  4765.7    0.07       0
Bank Sta=4760.4,4765.7
Exp/Cntr=0.3,0.1

Type RM Length L Ch R = 1,938,371,371,371
BEGIN DESCRIPTION:
Elm 01 29 1.0
END DESCRIPTION:
XS GIS Cut Line= 3
      1536823.87      6825220.74      1536599.14      6824077.42
      1536158.34      6823868.04
#Sta/Elev= 30
  4049.8 1851.49  4441.5 1847.16  4602.9 1847.34  4633.5 1846.78  4653.9 1847.23
  4684.5 1846.57  4690.8 1845.66  4695.9 1846.81  4704.8 1845.58  4715.0 1846.83
  4725.2 1847.38  4742.2 1846.21  4747.3 1846.79  4763.3 1844.84  4763.7 1844.34
  4768.2 1844.34  4768.6 1844.84  4786.4 1847.31  4837.3 1847.13  4857.7 1847.70
  4888.3 1847.63  4896.4 1847.50  4908.7 1846.20  4918.9 1847.08  4939.2 1846.92
  4947.8 1847.53  5041.2 1847.06  5352.4 1847.63  5463.5 1848.19  5703.0 1850.48
#Mann=4,-1,0
  4049.8   0.035       0  4441.5    0.07       0  4763.3    0.07       0
  4768.6    0.07       0
Bank Sta=4763.3,4768.6
Exp/Cntr=0.3,0.1

Type RM Length L Ch R = 1,567,0,0,0
BEGIN DESCRIPTION:
Elm 01 29 763.266
END DESCRIPTION:
XS GIS Cut Line= 3
      1537232.08      6825111.72      1536911.06      6824042.41
      1536223.20      6823800.27
#Sta/Elev= 30
  4116.4 1848.96  4203.0 1847.43  4289.2 1846.56  4397.0 1845.11  4628.0 1845.49
  4641.2 1844.86  4667.0 1845.67  4789.1 1846.39  4809.4 1845.20  4816.9 1846.22
  4855.2 1846.42  4872.0 1845.61  4903.4 1845.98  4918.6 1844.48  4919.0 1843.98
  4924.0 1844.48  4926.5 1845.28  4945.1 1844.84  4954.3 1846.18  4976.4 1844.72
  4990.7 1844.92  5007.8 1846.21  5063.9 1844.94  5239.3 1847.18  5271.1 1846.56
  5325.4 1847.85  5345.3 1847.19  5382.0 1847.85  5619.1 1847.78  5962.1 1850.14
#Mann=9,-1,0
  4116.4   0.035       0  4203.0    0.16       0  4289.2    0.07       0
  4397.0   0.035       0  4628.0    0.07       0  4667.0   0.035       0
  4918.6    0.07       0  4924.0   0.035       0  4990.7    0.07       0
Bank Sta=4918.6,4924
Exp/Cntr=0.3,0.1

Chan Stop Cuts=-1