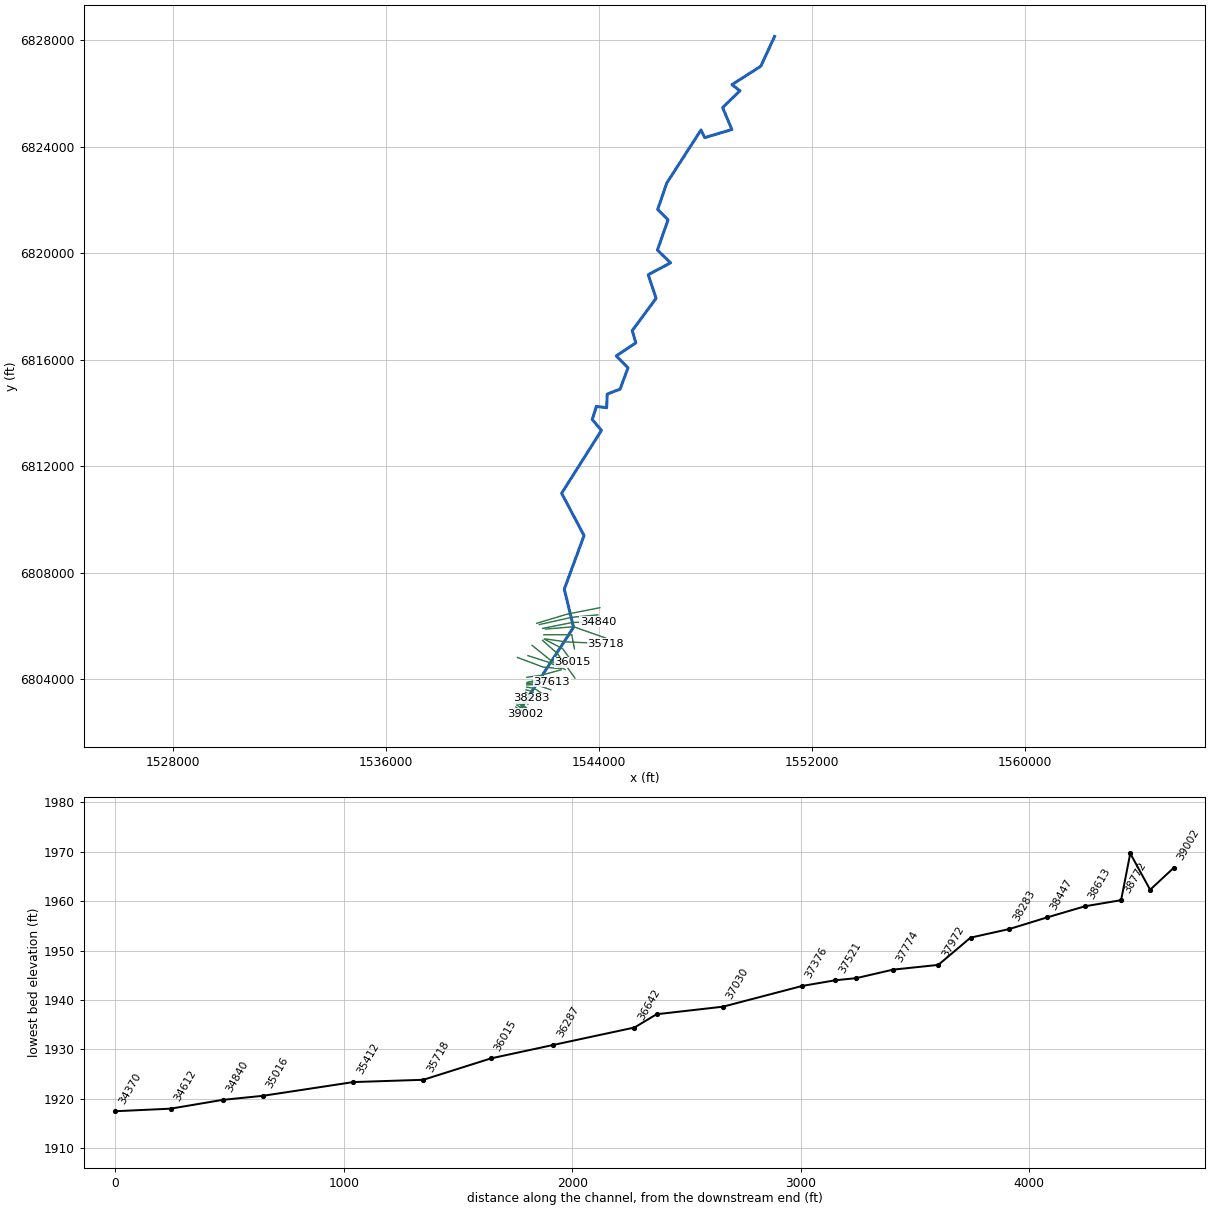
--- Elm 01 30.prj (project) ---

Proj Title=Elm 01 30 Base Level Engineering
Current Plan=p01
Default Exp/Contr=0.3,0.1
English Units
Geom File=g01
Flow File=f01
Plan File=p01
Y Axis Title=Elevation
X Axis Title(PF)=Main Channel Distance
X Axis Title(XS)=Station
BEGIN DESCRIPTION:
Elm 01 30
END DESCRIPTION:
DSS Export Rating Curves= 0
DSS Export Rating Curve Sorted= 0
DSS Export Volume Flow Curves= 0
DXF OffsetX= 0
DXF OffsetY= 0
DXF ScaleX= 1
DXF ScaleY= 10

--- Elm 01 30.p01 (plan) ---

Plan Title=Multiple Run
Program Version=4.10
Short Identifier=Multiple
Geom File=g01
Flow File=f01
Subcritical Flow
K Sum by GR= 0
Std Step Tol= 0.01
Critical Tol= 0.01
Num of Std Step Trials= 20
Max Error Tol= 0.3
Flow Tol Ratio= 0.001
Split Flow NTrial= 30
Split Flow Tol= 0.02
Split Flow Ratio= 0.02
Log Output Level= 0
Friction Slope Method= 1
Unsteady Friction Slope Method= 2
Unsteady Bridges Friction Slope Method= 1
Parabolic Critical Depth
Global Vel Dist= 1 , 1 , 1
Global Log Level= 0
CheckData=True
Encroach Param=-1 ,0,0, 0
BEGIN DESCRIPTION:
Multiple Run
END DESCRIPTION:
Computation Interval=1HOUR
Output Interval=1HOUR
Run HTab= 0
Run UNet= 0
Run PostProcess= 0
Run WQNet= 0
UNET Theta= 1
UNET Theta Warmup= 1
UNET ZTol= 0.02
UNET ZSATol= 0.05
UNET MxIter= 20
UNET MaxInSteps= 0
UNET DtIC= 0
UNET DtMin= 0
UNET MaxCRTS= 20
UNET WFStab= 2
UNET SFStab= 1
UNET WFX= 1
UNET SFX= 1
UNET DSS MLevel= 4
UNET DZMax Abort= 100
UNET Convert EG Bridges= 0
UNET Use Existing IB Tables=-1
UNET Froude Reduction=False
UNET Froude Limit= 1
UNET Froude Power= 10
UNET Time Slicing=0,0, 5
UNET Junction Losses=0
Instantaneous Interval=1HOUR
Write IC File= 0
Write IC File at Sim End=0
Echo Input=False
Echo Parameters=False
Echo Output=False
Write Detailed= 0
WQ AD Non Conservative
WQ ULTIMATE=-1
WQ Max Comp Step=1HOUR
WQ Output Interval=15MIN
WQ Output Selected Increments= 0
WQ Output face flow=0
WQ Output face velocity=0
WQ Output face area=0
WQ Output face dispersion=0
WQ Output cell volume=0
WQ Output cell surface area=0
WQ Output cell continuity=0
WQ Output cumulative cell continuity=0
WQ Output face conc=0
WQ Output face dconc_dx=0
WQ Output face courant=0
WQ Output face peclet=0
WQ Output face adv mass=0
WQ Output face disp mass=0
WQ Output cell mass=0
WQ Output cell source sink temp=0
WQ Output cell source sink nsm=0
WQ Output MaxMinRange=-1
WQ Daily Max Min Mean=-1
WQ Daily Range=0
WQ Daily Time=0
WQ Create Restart=0
WQ Fixed Restart=0
WQ System Summary=0
WQ Use Fixed Temperature=0
Sorting and Armoring Iterations= 10
XS Update Threshold= 0.02
Hydraulics Update Threshold= 0.02
Energy Slope Method= 1
Volume Change Method= 0
XS Weighting Method= 0
Number of US Weighted Cross Sections= 1
Number of DS Weighted Cross Sections= 1
Upstream XS Weight=0.25
Main XS Weight=0.5
Downstream XS Weight=0.25
Number of DS XS's Weighted with US Boundary= 1
Upstream Boundary Weight= 1
Weight of XSs Associated with US Boundary= 0
Number of US XS's Weighted with DS Boundary= 1
Downstream Boundary Weight= 0.5
Weight of XSs Associated with DS Boundary= 0.5
Sediment Output Level= 4
Mass or Volume Output= 0
Output Increment Type= 1
Profile and TS Output Increment= 10
XS Output Flag= 0
XS Output Increment= 10
Disregard all LS=0
Disregard all Conn=0
Disregard all Breaches=0
Disregard all Pumps=0

--- Elm 01 30.f01 (steady flow) ---

Flow Title=Multiple
Number of Profiles=7
Profile Names=10-year,25-year,50-year,1pct_min,100-year,1pct_plu,500-year
River Rch & RM= Elm 01 30,Reach-1,39002
     367     532     675     532     853    1170    1380
River Rch & RM= Elm 01 30,Reach-1,36642
     533     788    1010     809    1300    1780    2150
River Rch & RM= Elm 01 30,Reach-1,32210
     705    1060    1370    1100    1760    2420    2960
River Rch & RM= Elm 01 30,Reach-1,29129
     794    1190    1540    1240    1980    2730    3320
River Rch & RM= Elm 01 30,Reach-1,24780
     813    1210    1560    1240    1990    2740    3290
River Rch & RM= Elm 01 30,Reach-1,16180
     800    1180    1520    1200    1930    2650    3160
River Rch & RM= Elm 01 30,Reach-1,9764
     838    1230    1580    1250    2000    2750    3260
River Rch & RM= Elm 01 30,Reach-1,3518
    1120    1660    2140    1700    2720    3750    4490
Boundary for River Rch & Prof#=Elm 01 30,Reach-1,1
Up Type=0
Dn Type=3
Dn Slope=0.0066
Boundary for River Rch & Prof#=Elm 01 30,Reach-1,2
Up Type=0
Dn Type=3
Dn Slope=0.0066
Boundary for River Rch & Prof#=Elm 01 30,Reach-1,3
Up Type=0
Dn Type=3
Dn Slope=0.0066
Boundary for River Rch & Prof#=Elm 01 30,Reach-1,4
Up Type=0
Dn Type=3
Dn Slope=0.0066
Boundary for River Rch & Prof#=Elm 01 30,Reach-1,5
Up Type=0
Dn Type=3
Dn Slope=0.0066
Boundary for River Rch & Prof#=Elm 01 30,Reach-1,6
Up Type=0
Dn Type=3
Dn Slope=0.0066
Boundary for River Rch & Prof#=Elm 01 30,Reach-1,7
Up Type=0
Dn Type=3
Dn Slope=0.0066

--- Elm 01 30.g01 (geometry) ---

Geom Title=Existing Conditions
Program Version=4.10

River Reach=Elm 01 30       ,Reach-1
Reach XY= 30
        1540905.        6802638.      1543053.37      6805944.04
      1542705.09      6807372.61      1543447.47      6809388.01
      1542606.04      6810977.56      1544101.55      6813339.49
      1543755.96      6813748.27      1543910.42      6814240.75
      1544296.53      6814190.66      1544318.37      6814701.79
      1544801.96      6814889.36      1545097.72       6815688.1
      1544658.53      6816136.55      1545393.92      6816627.95
      1545258.12      6817086.84       1546153.5      6818299.53
      1545857.99       6819186.6      1546697.58      6819634.56
      1546204.37      6820113.07      1546604.63      6821253.28
      1546212.28      6821637.91       1546558.1      6822636.35
      1547841.76      6824624.65      1547979.99      6824337.33
      1548999.98      6824642.93      1548654.32      6825467.92
      1549303.85      6826097.67       1549005.7       6826328.2
      1550088.79      6827021.29        1550605.        6828138.

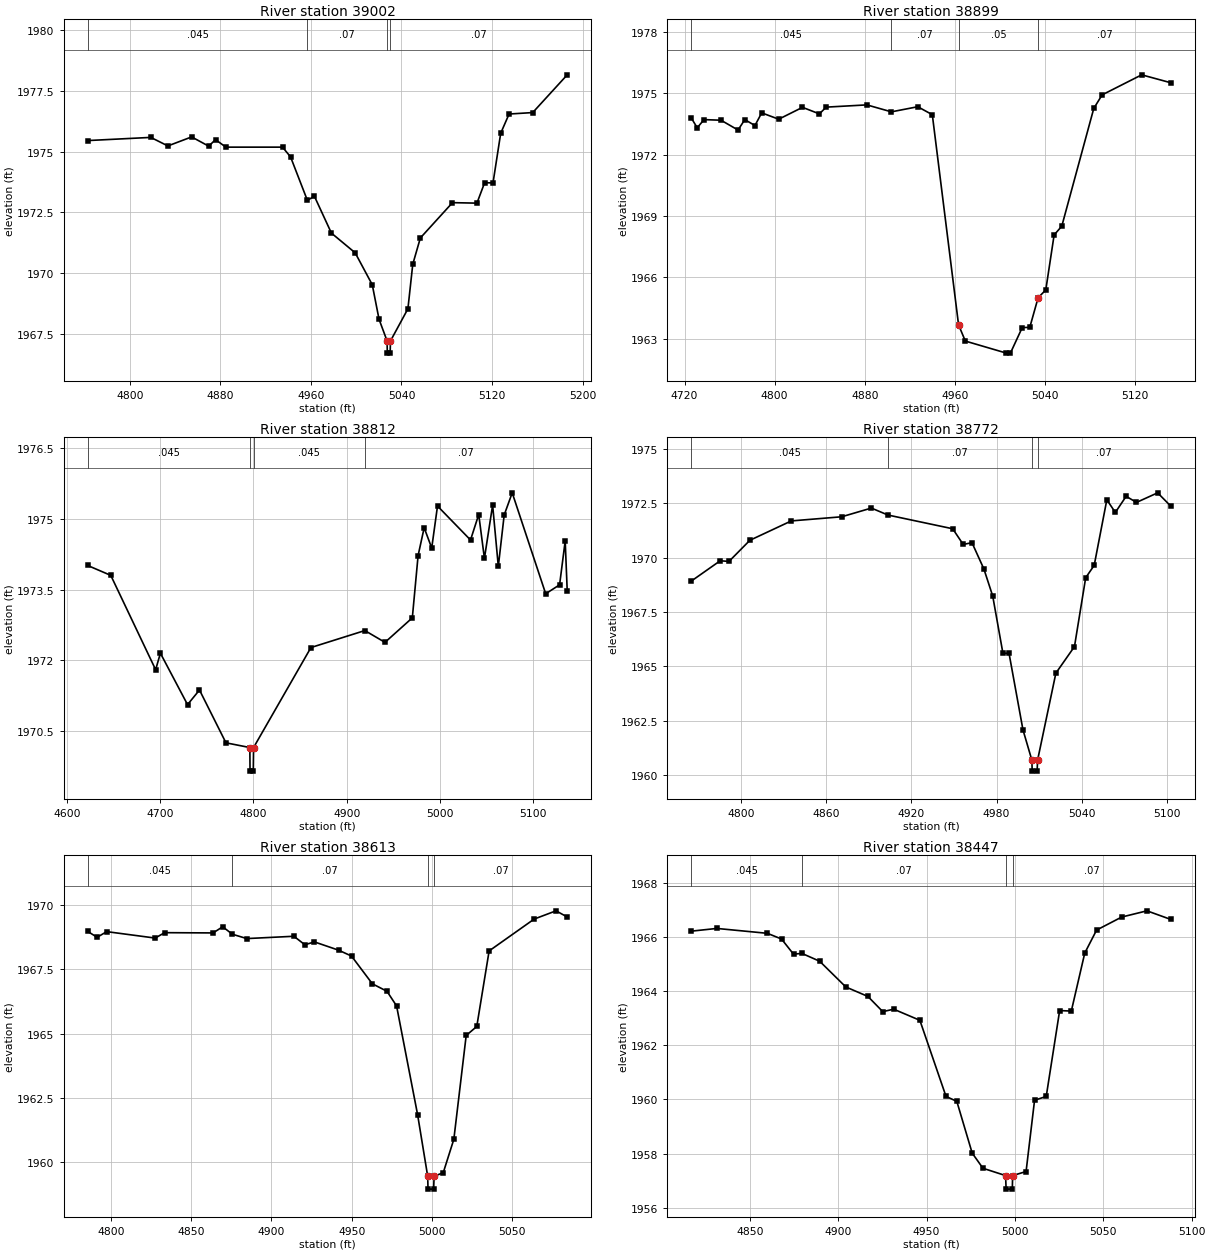
Type RM Length L Ch R = 1 ,39002   ,103,103,103
BEGIN DESCRIPTION:
Elm 01 30 15.0
END DESCRIPTION:
XS GIS Cut Line= 3
      1540881.32      6802942.36      1541117.46      6802786.46
       1541221.7      6802691.76
#Sta/Elev= 30
  4762.7 1975.45  4818.5 1975.58  4833.6 1975.23  4854.6  1975.6  4869.7 1975.22
  4875.7 1975.49  4884.8 1975.18  4934.9 1975.18    4942 1974.78  4956.9 1972.99
    4963 1973.17  4978.1 1971.65  4999.1 1970.84  5014.2 1969.53  5020.2 1968.11
  5027.3 1967.22  5027.5 1966.72    5030 1966.72  5030.3 1967.22  5045.7 1968.54
    5050 1970.37  5056.7 1971.45  5085.1  1972.9  5106.7 1972.88  5113.5 1973.72
  5120.9 1973.71  5127.7 1975.75  5135.1 1976.54    5156  1976.6  5186.5 1978.15
#Mann= 4 ,-1 , 0
  4762.7    .045       0  4956.9     .07       0  5027.3     .07       0
  5030.3     .07       0
Bank Sta=5027.3,5030.3
XS Rating Curve= 0 ,0
Exp/Cntr=0.3,0.1

Type RM Length L Ch R = 1 ,38899   ,87,87,87
BEGIN DESCRIPTION:
Elm 01 30 38929.284
END DESCRIPTION:
XS GIS Cut Line= 3
      1540926.56      6803016.51      1541162.72       6802860.6
      1541268.28       6802764.7
#Sta/Elev= 30
  4726.1 1973.79  4731.3 1973.32  4737.3 1973.72  4752.4 1973.69  4767.5 1973.21
  4773.5 1973.72  4782.5 1973.43  4788.5 1974.05  4803.6 1973.74  4824.7 1974.32
  4839.7    1974  4845.7 1974.33  4881.8 1974.44  4903.6  1974.1    4927 1974.35
  4939.9 1973.96  4963.2 1963.68  4969.2 1962.89  5005.7  1962.3  5009.2  1962.3
  5019.7 1963.55  5026.4 1963.56  5033.8 1965.01  5040.6 1965.39    5048 1968.08
  5054.8 1968.51  5083.2 1974.27  5090.6 1974.93  5125.7 1975.91  5151.7 1975.52
#Mann= 4 ,-1 , 0
  4726.1    .045       0  4903.6     .07       0  4963.2     .05       0
  5033.8     .07       0
Bank Sta=4963.2,5033.8
XS Rating Curve= 0 ,0
Exp/Cntr=0.3,0.1

Type RM Length L Ch R = 1 ,38812   ,40,40,40
BEGIN DESCRIPTION:
Elm 01 30 10.0
END DESCRIPTION:
XS GIS Cut Line= 4
      1540830.86      6803100.53      1541027.89      6803052.94
      1541186.32      6802935.84      1541280.73      6802871.06
#Sta/Elev= 30
  4622.3 1974.01  4647.1  1973.8  4695.2  1971.8  4700.3 1972.15  4729.4 1971.06
  4742.2 1971.37  4770.6 1970.25  4796.2 1970.15  4796.4 1969.65  4799.9 1969.65
  4800.2 1970.15  4861.7 1972.27  4919.5 1972.63  4941.1 1972.38  4970.4  1972.9
  4976.6 1974.22  4983.1 1974.81  4991.2 1974.38  4997.4 1975.27  5032.8 1974.55
  5041.6 1975.09  5047.7 1974.16  5056.5 1975.29  5062.6 1973.99  5068.9 1975.08
  5077.5 1975.55  5113.4 1973.41  5128.3  1973.6  5134.3 1974.53  5136.5 1973.46
#Mann= 4 ,-1 , 0
  4622.3    .045       0  4796.2     .07       0  4800.2    .045       0
  4919.5     .07       0
Bank Sta=4796.2,4800.2
XS Rating Curve= 0 ,0
Exp/Cntr=0.3,0.1

Type RM Length L Ch R = 1 ,38772   ,159,159,159
BEGIN DESCRIPTION:
Elm 01 30 38772.31
END DESCRIPTION:
XS GIS Cut Line= 3
      1541006.97      6803117.54      1541186.96       6802984.5
      1541281.03      6802919.96
#Sta/Elev= 30
    4765 1968.92  4785.3 1969.85  4791.5 1969.82  4806.2 1970.79  4835.4 1971.68
  4870.9 1971.87  4891.8 1972.27  4903.5 1971.95  4949.1 1971.32  4956.5  1970.6
  4962.7 1970.68  4971.1 1969.47  4977.3 1968.23  4984.5  1965.6  4988.8  1965.6
  4998.6 1962.09  5004.9 1960.69  5005.1 1960.19  5008.6 1960.19  5008.9 1960.69
  5021.8 1964.69  5034.9 1965.91  5042.8 1969.07  5048.8 1969.64  5057.7 1972.65
  5063.7 1972.07  5071.3 1972.81  5078.6 1972.53  5093.5 1972.97  5102.9 1972.35
#Mann= 4 ,-1 , 0
    4765    .045       0  4903.5     .07       0  5004.9     .07       0
  5008.9     .07       0
Bank Sta=5004.9,5008.9
XS Rating Curve= 0 ,0
Exp/Cntr=0.3,0.1

Type RM Length L Ch R = 1 ,38613   ,166,166,166
BEGIN DESCRIPTION:
Elm 01 30 38612.91
END DESCRIPTION:
XS GIS Cut Line= 3
      1541097.68      6803227.99      1541269.43      6803114.71
      1541340.73      6803054.61
#Sta/Elev= 30
  4785.4 1968.98  4791.3 1968.75  4797.3 1968.97  4827.5 1968.72  4833.4 1968.93
  4863.6 1968.92  4869.6 1969.16  4875.6 1968.87  4884.6  1968.7    4914 1968.79
  4920.8 1968.46  4926.8 1968.57  4941.8 1968.25  4949.9 1968.02  4962.9 1966.94
    4972 1966.65    4978 1966.08  4991.1 1961.85  4997.4 1959.45  4997.6 1958.95
  5001.1 1958.95  5001.4 1959.45  5007.1 1959.59  5013.7 1960.89  5021.4 1964.93
    5028 1965.28  5035.7 1968.22  5063.8 1969.46  5077.4 1969.78  5084.4 1969.54
#Mann= 4 ,-1 , 0
  4785.4    .045       0  4875.6     .07       0  4997.4     .07       0
  5001.4     .07       0
Bank Sta=4997.4,5001.4
XS Rating Curve= 0 ,0
Exp/Cntr=0.3,0.1

Type RM Length L Ch R = 1 ,38447   ,164,164,164
BEGIN DESCRIPTION:
Elm 01 30 38447.04
END DESCRIPTION:
XS GIS Cut Line= 3
      1541203.22      6803356.56      1541356.24      6803249.26
        1541420.      6803193.79
#Sta/Elev= 30
  4816.9 1966.21  4831.3 1966.31  4859.9 1966.13  4867.9 1965.92  4874.7 1965.36
  4879.4 1965.39  4889.5  1965.1  4904.3 1964.15  4916.8  1963.8  4925.2 1963.24
  4931.4 1963.33  4946.2 1962.92    4961 1960.11  4967.1 1959.93  4975.8 1958.02
  4981.9 1957.46  4994.7 1957.19    4995 1956.69  4998.5 1956.69  4998.7 1957.19
  5006.3 1957.34  5011.1 1959.97  5017.7 1960.11  5025.3 1963.28  5031.9 1963.26
  5039.5  1965.4  5046.2 1966.25  5060.4 1966.73  5074.7 1966.96  5088.3 1966.64
#Mann= 4 ,-1 , 0
  4816.9    .045       0  4879.4     .07       0  4994.7     .07       0
  4998.7     .07       0
Bank Sta=4994.7,4998.7
XS Rating Curve= 0 ,0
Exp/Cntr=0.3,0.1

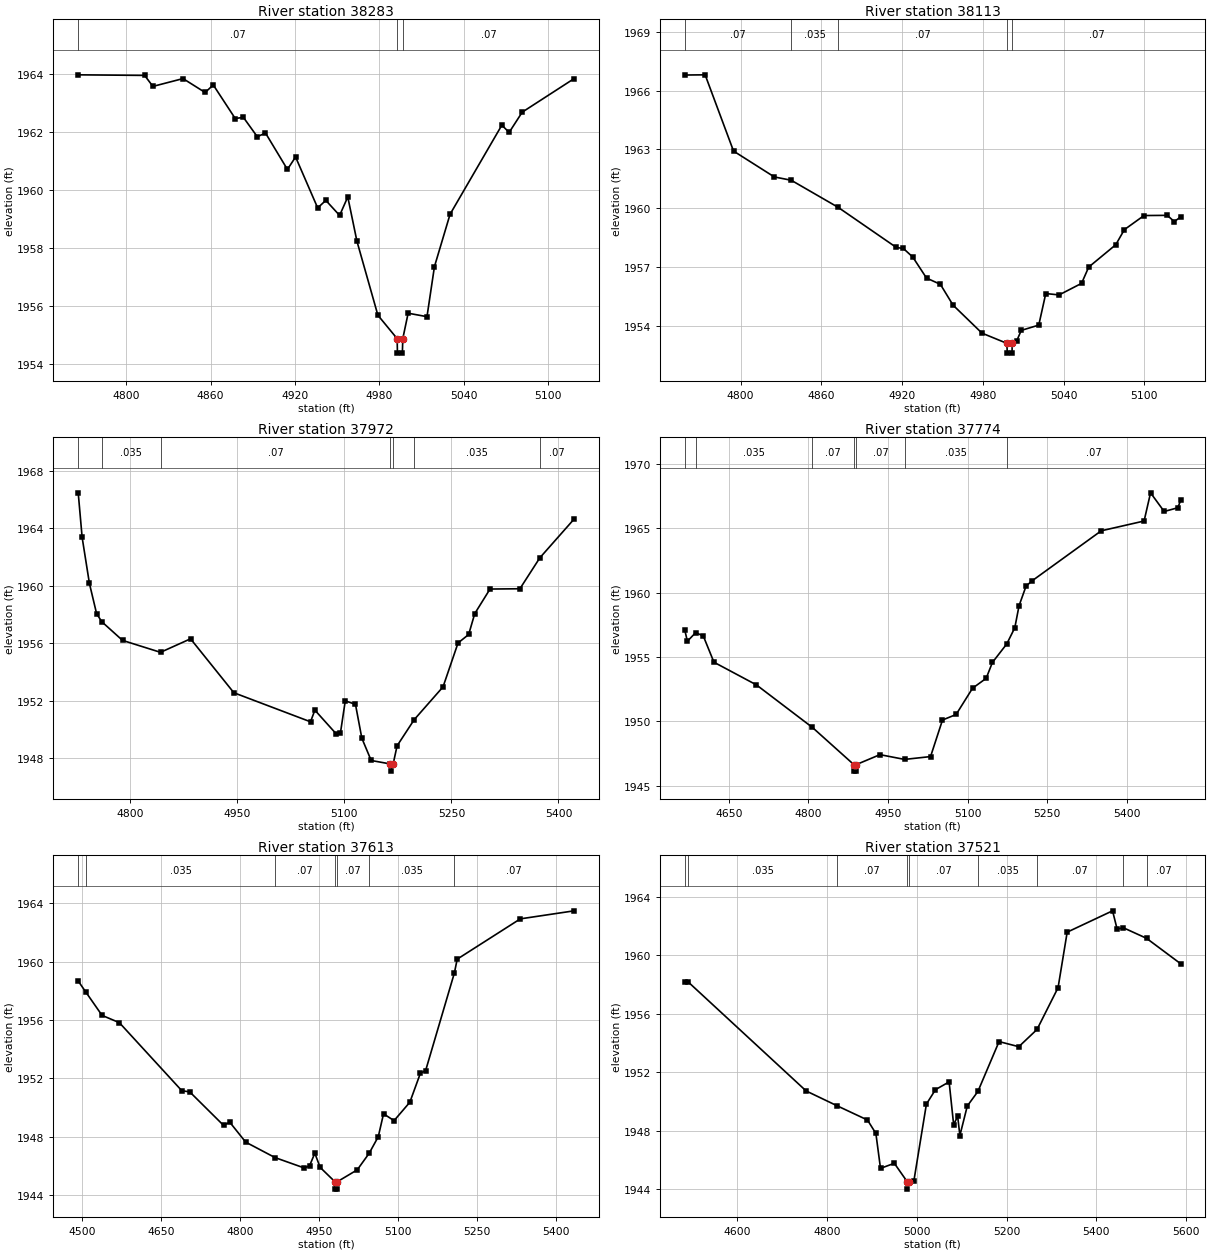
Type RM Length L Ch R = 1 ,38283   ,170,170,170
BEGIN DESCRIPTION:
Elm 01 30 38244.4
END DESCRIPTION:
XS GIS Cut Line= 3
       1541244.4      6803500.06      1541457.82      6803374.03
      1541481.35      6803272.07
#Sta/Elev= 30
  4765.9 1963.98  4813.1 1963.96    4819 1963.58  4840.4 1963.85  4856.1 1963.37
  4861.9 1963.63  4877.5 1962.47  4883.3 1962.51  4893.2 1961.84    4899 1961.97
  4914.6 1960.71  4920.4 1961.14  4936.1 1959.38  4941.9 1959.64  4951.7 1959.12
  4957.5 1959.76    4964 1958.23  4978.9 1955.67  4992.6 1954.86  4992.8 1954.36
  4996.3 1954.36  4996.6 1954.86  5000.4 1955.74  5013.8 1955.62  5019.1 1957.35
  5030.2 1959.16    5067 1962.24  5072.2 1961.99  5081.5 1962.69  5118.4 1963.85
#Mann= 3 ,-1 , 0
  4765.9     .07       0  4992.6     .07       0  4996.6     .07       0
Bank Sta=4992.6,4996.6
XS Rating Curve= 0 ,0
Exp/Cntr=0.3,0.1

Type RM Length L Ch R = 1 ,38113   ,141,141,141
BEGIN DESCRIPTION:
Elm 01 30 38112.91
END DESCRIPTION:
XS GIS Cut Line= 3
      1541270.19      6803590.35      1541516.83      6803531.38
      1541552.66      6803422.19
#Sta/Elev= 30
  4758.5  1966.8  4773.7 1966.81  4794.8 1962.92  4825.1  1961.6  4837.7 1961.43
  4872.5 1960.05  4915.8    1958    4921 1957.95    4928 1957.51  4938.2 1956.44
  4948.5 1956.12  4957.9 1955.06  4979.4 1953.63  4997.9 1953.11  4998.2 1952.61
  5001.7 1952.61  5001.9 1953.11  5005.1 1953.22  5008.6 1953.77  5021.6 1954.04
  5026.8 1955.65  5036.7 1955.58  5053.4 1956.17  5058.7    1957  5078.8 1958.14
  5085.2 1958.91  5099.8 1959.63  5117.1 1959.64  5122.3 1959.32    5127 1959.56
#Mann= 5 ,-1 , 0
  4758.5     .07       0  4837.7    .035       0  4872.5     .07       0
  4997.9     .07       0  5001.9     .07       0
Bank Sta=4997.9,5001.9
XS Rating Curve= 0 ,0
Exp/Cntr=0.3,0.1

Type RM Length L Ch R = 1 ,37972   ,198,198,198
BEGIN DESCRIPTION:
Elm 01 30 37971.77
END DESCRIPTION:
XS GIS Cut Line= 3
      1541299.53      6803692.75      1541581.93      6803648.56
      1541920.16      6803418.48
#Sta/Elev= 30
  4727.1 1966.45  4732.6 1963.35  4742.8 1960.15  4752.9 1958.04  4760.3 1957.48
  4789.2 1956.19  4842.4 1955.36  4884.5  1956.3  4945.2 1952.55  5052.6 1950.53
  5058.7 1951.34  5088.6 1949.69  5094.6 1949.78  5101.3 1951.99  5115.6 1951.74
  5124.5 1949.39  5137.6 1947.84  5164.4  1947.6  5164.7  1947.1  5168.4  1947.6
  5173.9 1948.86  5197.9 1950.68  5238.3 1952.96  5259.3 1956.01  5274.2  1956.6
  5282.7 1958.05  5304.1 1959.76    5346 1959.78  5373.9 1961.93    5422 1964.63
#Mann= 7 ,-1 , 0
  4727.1     .07       0  4760.3    .035       0  4842.4     .07       0
  5164.4     .07       0  5168.4     .07       0  5197.9    .035       0
  5373.9     .07       0
Bank Sta=5164.4,5168.4
XS Rating Curve= 0 ,0
Exp/Cntr=0.3,0.1

Type RM Length L Ch R = 1 ,37774   ,161,161,161
BEGIN DESCRIPTION:
Elm 01 30 37774.31
END DESCRIPTION:
XS GIS Cut Line= 3
      1541299.93      6803776.37      1541620.99      6803796.13
      1542200.04      6803593.03
#Sta/Elev= 30
  4566.5 1957.13  4571.6 1956.23  4587.2  1956.9  4601.6 1956.64  4621.7  1954.6
  4701.8 1952.84  4807.5 1949.53  4885.7 1946.64  4885.9 1946.14  4889.4 1946.14
  4889.7 1946.64  4934.8 1947.42  4981.2 1947.05  5030.2 1947.27  5052.7 1950.11
  5078.4 1950.54  5109.4 1952.58  5135.1 1953.35  5146.8 1954.58  5173.9 1956.02
  5189.1 1957.28  5197.1 1958.99  5210.3 1960.51  5220.9  1960.9  5352.1 1964.81
  5432.9 1965.57  5445.1 1967.76  5470.8 1966.31  5496.5  1966.6  5501.8 1967.17
#Mann= 7 ,-1 , 0
  4566.5     .07       0  4587.2    .035       0  4807.5     .07       0
  4885.7    .035       0  4889.7     .07       0  4981.2    .035       0
  5173.9     .07       0
Bank Sta=4885.7,4889.7
XS Rating Curve= 0 ,0
Exp/Cntr=0.3,0.1

Type RM Length L Ch R = 1 ,37613   ,92,92,92
BEGIN DESCRIPTION:
Elm 01 30 37613.42
END DESCRIPTION:
XS GIS Cut Line= 3
       1541300.2      6803821.86      1541798.94      6803895.96
      1542237.31      6803891.62
#Sta/Elev= 30
    4492 1958.67  4506.6 1957.91  4537.3 1956.32  4570.2 1955.82  4688.9 1951.16
    4704 1951.08  4768.4 1948.78  4779.9 1949.01  4810.3 1947.64  4866.1 1946.58
  4921.5 1945.87  4931.6 1946.01  4941.7 1946.88  4951.8 1945.91  4980.1 1944.92
  4980.4 1944.42  4983.9 1944.42  4984.1 1944.92  5022.3 1945.74  5044.9 1946.87
  5062.3 1948.01  5072.3 1949.58  5092.3 1949.11  5122.3 1950.37  5142.3 1952.35
  5152.3 1952.54    5207 1959.23  5212.3 1960.17  5332.3 1962.93  5434.6 1963.48
#Mann= 7 ,-1 , 0
    4492     .07       0  4506.6    .035       0  4866.1     .07       0
  4980.1     .07       0  4984.1     .07       0  5044.9    .035       0
    5207     .07       0
Bank Sta=4980.1,4984.1
XS Rating Curve= 0 ,0
Exp/Cntr=0.3,0.1

Type RM Length L Ch R = 1 ,37521   ,145,145,145
BEGIN DESCRIPTION:
Elm 01 30 37520.55
END DESCRIPTION:
XS GIS Cut Line= 3
      1541300.53      6803869.25       1541794.6       6803987.1
      1542384.88      6804078.25
#Sta/Elev= 30
  4482.4 1958.14  4490.6 1958.16  4753.1 1950.71  4822.4 1949.69  4889.8 1948.72
  4908.5  1947.8  4918.8 1945.41  4949.6 1945.76  4978.5 1944.49  4978.7 1943.99
  4982.5 1944.49  4993.1 1944.54  5021.1 1949.81  5041.3  1950.8  5071.7 1951.33
  5081.8  1948.4  5090.7 1948.98  5095.7 1947.66  5112.2 1949.68  5135.9 1950.68
    5183 1954.09    5227 1953.74  5267.6 1954.92  5314.5 1957.78  5334.8 1961.58
  5435.9 1963.04  5446.1 1961.79  5460.1 1961.88  5511.6 1961.16  5587.6 1959.42
#Mann= 9 ,-1 , 0
  4482.4     .07       0  4490.6    .035       0  4822.4     .07       0
  4978.5     .07       0  4982.5     .07       0  5135.9    .035       0
  5267.6     .07       0  5460.1    .035       0  5511.6     .07       0
Bank Sta=4978.5,4982.5
XS Rating Curve= 0 ,0
Exp/Cntr=0.3,0.1

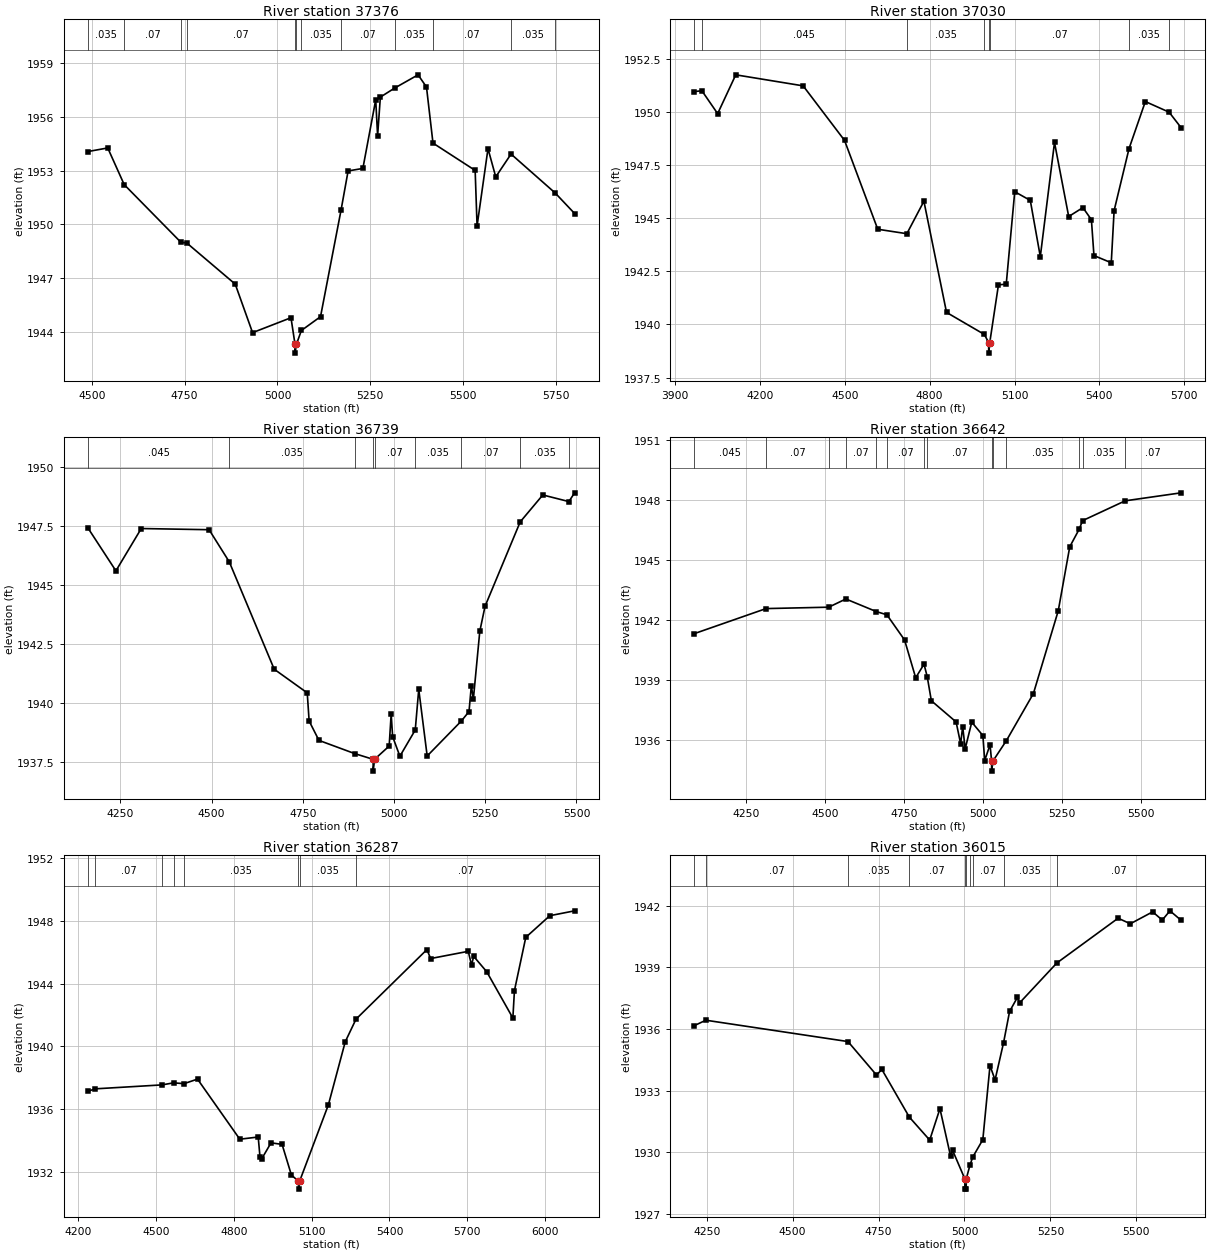
Type RM Length L Ch R = 1 ,37376   ,346,346,346
BEGIN DESCRIPTION:
Elm 01 30 37376.22
END DESCRIPTION:
XS GIS Cut Line= 3
      1541301.58      6804065.57      1541798.94      6804130.33
      1542580.06      6804342.97
#Sta/Elev= 30
  4489.5 1954.06  4542.7 1954.26    4587 1952.22  4739.8 1949.01  4755.7 1948.97
  4886.2 1946.68  4932.9 1943.98  5036.4 1944.81  5047.2 1943.34  5047.4 1942.84
  5051.2 1943.34  5064.4  1944.1    5116 1944.87  5171.2 1950.79  5190.3 1952.98
  5230.1 1953.12  5264.7 1956.94  5269.8 1954.94  5277.2 1957.09  5315.5 1957.59
  5378.8 1958.33  5401.5 1957.65    5419 1954.53  5532.6 1953.01  5537.8 1949.92
  5567.2 1954.22  5588.1 1952.65  5629.3 1953.92  5748.4 1951.75  5800.6 1950.61
#Mann= 12 ,-1 , 0
  4489.5    .035       0    4587     .07       0  4739.8    .035       0
  4755.7     .07       0  5047.2     .07       0  5051.2     .07       0
  5064.4    .035       0  5171.2     .07       0  5315.5    .035       0
    5419     .07       0  5629.3    .035       0  5748.4     .07       0
Bank Sta=5047.2,5051.2
XS Rating Curve= 0 ,0
Exp/Cntr=0.3,0.1

Type RM Length L Ch R = 1 ,37030   ,291,291,291
BEGIN DESCRIPTION:
Elm 01 30 37029.74
END DESCRIPTION:
XS GIS Cut Line= 3
      1540948.28      6804807.41      1541907.45      6804447.17
      1542600.92       6804386.5
#Sta/Elev= 30
  3968.3 1950.98  3994.5 1951.02  4050.3 1949.94  4114.3 1951.77  4352.6 1951.25
  4498.9 1948.68  4616.4 1944.49  4719.3 1944.28  4779.6 1945.81  4859.6 1940.57
  4993.4 1939.53  5008.5 1939.15  5008.8 1938.65  5012.5 1939.15  5043.2 1941.87
  5070.7  1941.9  5100.8 1946.26  5155.8 1945.85  5191.2  1943.2  5241.4 1948.58
  5291.6 1945.09  5341.8 1945.51  5371.9 1944.94  5380.9 1943.25  5442.1 1942.91
  5452.2 1945.37  5504.9 1948.29  5562.6 1950.51  5646.6 1950.01    5689 1949.28
#Mann= 8 ,-1 , 0
  3968.3     .07       0  3994.5    .045       0  4719.3    .035       0
  4993.4     .07       0  5008.5     .07       0  5012.5     .07       0
  5504.9    .035       0  5646.6     .07       0
Bank Sta=5008.5,5012.5
XS Rating Curve= 0 ,0
Exp/Cntr=0.3,0.1

Type RM Length L Ch R = 1 ,36739   ,97,97,97
BEGIN DESCRIPTION:
Elm 01 30 36739.28
END DESCRIPTION:
XS GIS Cut Line= 3
      1541338.84      6804876.87      1542137.49      6804620.78
      1542588.84      6804416.81
#Sta/Elev= 30
    4161  1947.4  4237.5 1945.59    4307 1947.38    4493 1947.33  4548.3 1945.97
  4671.5 1941.43    4762 1940.43  4767.2 1939.24  4794.1 1938.42  4892.4 1937.86
  4942.6 1937.62  4942.8 1937.12  4946.6 1937.62  4986.6 1938.18  4992.1 1939.54
  4996.1 1938.58    5016 1937.75  5058.1 1938.86  5067.7 1940.58  5090.8 1937.76
  5184.5 1939.24  5205.5 1939.64  5211.9 1940.74  5217.4 1940.16    5235 1943.03
  5249.4 1944.09  5345.8 1947.66  5407.8  1948.8  5479.2 1948.52    5495 1948.89
#Mann= 9 ,-1 , 0
    4161    .045       0  4548.3    .035       0  4892.4     .07       0
  4942.6     .07       0  4946.6     .07       0  5058.1    .035       0
  5184.5     .07       0  5345.8    .035       0  5479.2     .07       0
Bank Sta=4942.6,4946.6
XS Rating Curve= 0 ,0
Exp/Cntr=0.3,0.1

Type RM Length L Ch R = 1 ,36642   ,355,355,355
BEGIN DESCRIPTION:
Elm 01 30 36641.82
END DESCRIPTION:
XS GIS Cut Line= 3
      1541495.09      6805263.17      1542211.27      6804685.89
      1542735.38      6804352.37
#Sta/Elev= 30
  4086.1 1941.31  4312.8 1942.56  4511.2 1942.63  4565.5 1943.04  4662.1 1942.41
  4695.5 1942.25  4751.5 1940.99  4786.7  1939.1  4813.1 1939.78  4823.3 1939.15
  4836.3 1937.95  4914.7 1936.89  4929.1  1935.8  4935.5 1936.66  4943.5 1935.55
  4964.3 1936.88  4999.5 1936.21  5005.2 1934.96  5022.2 1935.75  5027.1 1934.93
  5027.3 1934.43  5031.1 1934.93  5074.1 1935.96  5159.5 1938.31  5238.2 1942.45
  5274.6 1945.65  5304.1 1946.52  5315.4 1946.96  5450.1 1947.95  5627.2 1948.35
#Mann= 14 ,-1 , 0
  4086.1    .045       0  4312.8     .07       0  4511.2    .035       0
  4565.5     .07       0  4662.1    .045       0  4695.5     .07       0
  4813.1    .035       0  4823.3     .07       0  5027.1     .07       0
  5031.1     .07       0  5074.1    .035       0  5304.1     .07       0
  5315.4    .035       0  5450.1     .07       0
Bank Sta=5027.1,5031.1
XS Rating Curve= 0 ,0
Exp/Cntr=0.3,0.1

Type RM Length L Ch R = 1 ,36287   ,272,272,272
BEGIN DESCRIPTION:
Elm 01 30 36287.19
END DESCRIPTION:
XS GIS Cut Line= 3
      1541890.11      6805449.76      1542449.99      6804950.65
      1543105.37      6804034.84
#Sta/Elev= 30
  4237.6 1937.15  4266.4  1937.3  4522.4 1937.55  4567.5 1937.68  4608.1 1937.63
  4659.8 1937.92  4822.9 1934.09  4893.9 1934.23  4900.6 1932.98  4908.1 1932.86
  4943.3 1933.86  4985.9 1933.76  5021.8 1931.81  5049.2 1931.41  5049.5 1930.91
  5053.4 1931.41  5164.4 1936.28  5229.5  1940.3    5271 1941.74  5544.3 1946.17
  5558.7  1945.6  5703.7 1946.06  5716.4 1945.18  5724.6 1945.74  5774.9 1944.76
  5875.7 1941.81  5881.8 1943.56  5925.5 1946.95  6018.2 1948.33  6113.8 1948.64
#Mann= 8 ,-1 , 0
  4237.6    .045       0  4266.4     .07       0  4522.4    .045       0
  4567.5     .07       0  4608.1    .035       0  5049.2    .035       0
  5053.4    .035       0    5271     .07       0
Bank Sta=5049.2,5053.4
XS Rating Curve= 0 ,0
Exp/Cntr=0.3,0.1

Type RM Length L Ch R = 1 ,36015   ,297,297,297
BEGIN DESCRIPTION:
Elm 01 30 36013.79
END DESCRIPTION:
XS GIS Cut Line= 3
      1541950.88      6805497.51       1542645.3      6805137.28
      1543016.72      6804623.58
#Sta/Elev= 30
  4214.2 1936.17  4247.4 1936.43    4661 1935.39  4743.9 1933.76  4759.6 1934.03
  4839.5 1931.71  4898.8 1930.59  4928.6 1932.12  4959.5 1929.81  4965.2  1930.1
    5001  1928.7  5001.3  1928.2  5004.9  1928.2  5005.2  1928.7  5015.8 1929.36
    5024 1929.76  5053.4 1930.61  5074.3 1934.22    5089 1933.52  5113.7 1935.33
  5131.3 1936.86    5154 1937.54  5160.2 1937.27  5268.9 1939.22  5447.1  1941.4
  5482.7 1941.13  5547.7 1941.71  5575.6 1941.31    5598 1941.76  5630.4  1941.3
#Mann= 10 ,-1 , 0
  4214.2    .045       0  4247.4     .07       0    4661    .035       0
  4839.5     .07       0    5001     .07       0  5005.2     .07       0
  5015.8    .035       0    5024     .07       0  5113.7    .035       0
  5268.9     .07       0
Bank Sta=5001,5005.2
XS Rating Curve= 0 ,0
Exp/Cntr=0.3,0.1

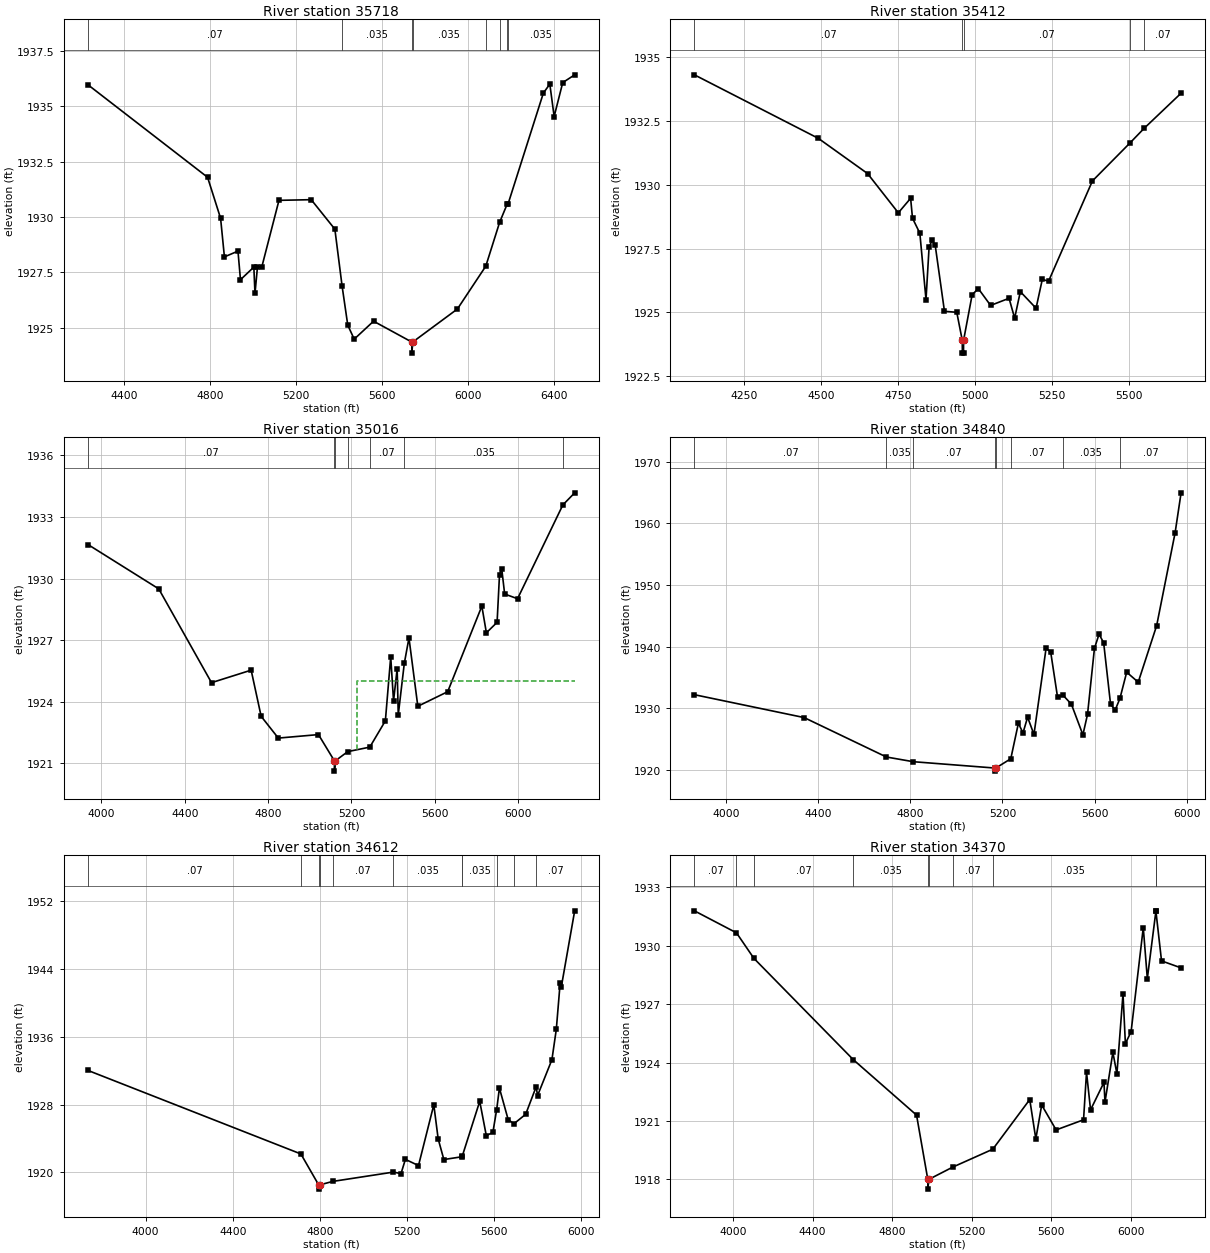
Type RM Length L Ch R = 1 ,35718   ,306,306,306
BEGIN DESCRIPTION:
Elm 01 30 35717.8
END DESCRIPTION:
XS GIS Cut Line= 3
      1541994.29       6805506.2      1542758.15      6805393.35
      1544250.56      6805332.62
#Sta/Elev= 30
  4230.8 1935.96  4787.5 1931.79  4848.1 1929.94  4865.9  1928.2    4929 1928.46
  4940.6 1927.17  5002.9 1927.74  5008.2 1926.55  5019.8 1927.75  5039.8 1927.74
  5119.9 1930.75    5270 1930.78  5380.1 1929.45  5413.7 1926.89  5440.2 1925.12
  5470.2 1924.49  5560.3  1925.3  5738.3 1924.36  5738.6 1923.86  5742.5 1924.36
  5950.6 1925.85  6082.7 1927.78  6147.2 1929.76  6181.9 1930.57  6186.9  1930.6
  6350.9 1935.59  6380.9 1935.99    6401 1934.53    6441 1936.06  6496.6 1936.41
#Mann= 8 ,-1 , 0
  4230.8     .07       0  5413.7    .035       0  5738.3     .07       0
  5742.5    .035       0  6082.7     .07       0  6147.2    .035       0
  6181.9     .07       0  6186.9    .035       0
Bank Sta=5738.3,5742.5
XS Rating Curve= 0 ,0
Exp/Cntr=0.3,0.1

Type RM Length L Ch R = 1 ,35412   ,396,396,396
BEGIN DESCRIPTION:
Elm 01 30 35403.88
END DESCRIPTION:
XS GIS Cut Line= 3
      1541942.17      6805662.45      1542986.24      6805663.26
      1543086.47      6805134.85
#Sta/Elev= 30
  4087.3 1934.31  4490.1 1931.82  4650.1 1930.44  4750.1  1928.9  4790.1 1929.47
  4796.2 1928.69  4820.1  1928.1  4840.1  1925.5  4850.1 1927.55  4860.1 1927.83
  4870.1 1927.62  4900.1 1925.04  4940.1    1925    4958  1923.9  4958.3  1923.4
    4962  1923.4  4962.2  1923.9  4990.1 1925.69  5010.1 1925.93  5050.1 1925.27
  5110.1 1925.55  5128.2 1924.77  5146.7 1925.81  5197.8 1925.16  5218.1 1926.29
  5238.5 1926.22    5381 1930.15  5502.4 1931.63  5548.9 1932.21  5669.2 1933.59
#Mann= 5 ,-1 , 0
  4087.3     .07       0    4958     .07       0  4962.2     .07       0
  5502.4    .035       0  5548.9     .07       0
Bank Sta=4958,4962.2
XS Rating Curve= 0 ,0
Exp/Cntr=0.3,0.1

Type RM Length L Ch R = 1 ,35016   ,176,176,176
BEGIN DESCRIPTION:
Elm 01 30 35016.1
END DESCRIPTION:
XS GIS Cut Line= 3
      1541994.29      6805875.13      1543057.62      6805961.93
      1544255.52      6805540.93
#Sta/Elev= 30
  3935.4 1931.66  4275.1  1929.5  4528.4 1924.93  4718.7 1925.54  4766.7 1923.29
  4849.1 1922.23  5041.9  1922.4  5118.4 1921.12  5118.7 1920.62  5122.6 1921.12
  5182.4 1921.57  5288.4 1921.79  5363.1 1923.07  5388.8 1926.19  5402.3 1924.04
  5419.7 1925.61    5425 1923.36    5454 1925.87  5476.4 1927.11  5518.9 1923.78
  5662.3 1924.49  5826.3 1928.66  5848.1 1927.36  5899.5 1927.87  5911.1 1930.19
  5921.7 1930.48  5935.8 1929.25  5997.7 1929.02  6215.2 1933.59    6272 1934.18
#Mann= 7 ,-1 , 0
  3935.4     .07       0  5118.4     .07       0  5122.6     .07       0
  5182.4    .035       0  5288.4     .07       0    5454    .035       0
  6215.2     .07       0
#XS Ineff= 2 , 0
       0                    5225       0    1925
Permanent Ineff=
       F       F
Bank Sta=5118.4,5122.6
XS Rating Curve= 0 ,0
Exp/Cntr=0.3,0.1

Type RM Length L Ch R = 1 ,34840   ,228,228,228
BEGIN DESCRIPTION:
Elm 01 30 34840.28
END DESCRIPTION:
XS GIS Cut Line= 3
      1541890.09      6805901.17      1543009.88      6806122.52
      1543981.04      6806152.87
#Sta/Elev= 30
  3862.8  1932.2  4339.1 1928.49  4696.5 1922.09  4812.9 1921.33  5167.4  1920.3
  5167.6  1919.8  5171.6  1920.3  5236.5 1921.81  5269.5 1927.57  5289.5 1925.99
  5309.5 1928.55  5337.1 1925.75  5389.6  1939.7  5409.6 1939.16  5439.6 1931.79
  5462.7 1932.14  5499.6 1930.66  5549.6 1925.69  5569.7 1929.01  5599.7 1939.71
  5619.7 1942.02  5639.7 1940.63  5669.7 1930.66  5689.7 1929.71  5710.4 1931.59
  5739.7 1935.85  5789.8 1934.23  5869.8  1943.4  5949.8 1958.43  5975.9 1964.95
#Mann= 8 ,-1 , 0
  3862.8     .07       0  4696.5    .035       0  4812.9     .07       0
  5167.4     .07       0  5171.6     .07       0  5236.5     .07       0
  5462.7    .035       0  5710.4     .07       0
Bank Sta=5167.4,5171.6
XS Rating Curve= 0 ,0
Exp/Cntr=0.3,0.1

Type RM Length L Ch R = 1 ,34612   ,242,242,242
BEGIN DESCRIPTION:
Elm 01 30 34612.13
END DESCRIPTION:
XS GIS Cut Line= 3
      1541768.58       6806044.4      1542996.86      6806317.83
      1543969.05      6806408.98
#Sta/Elev= 30
  3735.3 1932.02  4712.8 1922.17  4794.5 1918.52  4794.9 1918.02  4799.6 1918.52
  4859.1 1918.93  5137.9 1920.03  5172.6 1919.85  5192.7 1921.53  5252.9  1920.8
  5323.2 1927.97  5343.3 1923.94  5369.4 1921.51  5452.9 1921.84  5454.3 1921.94
  5534.1 1928.38  5564.3 1924.33  5594.4 1924.71  5611.9  1927.4  5624.5 1929.94
  5664.7 1926.22  5691.1 1925.73  5745.1 1926.85  5793.3  1930.1  5799.6 1929.05
  5865.6 1933.29  5885.7 1936.86  5903.4 1942.34  5908.4 1941.83  5970.1 1950.85
#Mann= 11 ,-1 , 0
  3735.3     .07       0  4712.8    .035       0  4794.5     .07       0
  4799.6    .035       0  4859.1     .07       0  5137.9    .035       0
  5452.9     .07       0  5454.3    .035       0  5611.9     .07       0
  5691.1    .035       0  5793.3     .07       0
Bank Sta=4794.5,4799.6
XS Rating Curve= 0 ,0
Exp/Cntr=0.3,0.1

Type RM Length L Ch R = 1 ,34370   ,242,242,242
BEGIN DESCRIPTION:
Elm 01 30 34369.59
END DESCRIPTION:
XS GIS Cut Line= 3
      1541668.76      6806092.15      1542810.23      6806435.02
      1544041.47       6806677.8
#Sta/Elev= 30
  3806.2 1931.79  4017.7 1930.66  4105.3 1929.35  4604.8 1924.15  4923.1  1921.3
  4979.6    1918    4980  1917.5  4984.7    1918  5104.9 1918.63  5306.4 1919.55
  5492.2  1922.1  5522.7 1920.08  5552.2 1921.82  5624.7 1920.54  5762.6 1921.06
  5777.6  1923.5  5797.9 1921.57  5865.3 1922.98  5870.4 1921.97  5910.1 1924.52
  5930.4 1923.42    5961 1927.53    5973 1924.97  6001.8 1925.59  6062.9 1930.93
  6083.3 1928.31  6126.4 1931.77  6126.5 1931.77  6154.7 1929.22    6253 1928.86
#Mann= 10 ,-1 , 0
  3806.2     .07       0  4017.7    .035       0  4105.3     .07       0
  4604.8    .035       0  4979.6    .035       0  4984.7    .035       0
  5104.9     .07       0  5306.4    .035       0  6126.4     .07       0
  6126.5    .035       0
Bank Sta=4979.6,4984.7
XS Rating Curve= 0 ,0
Exp/Cntr=0.3,0.1