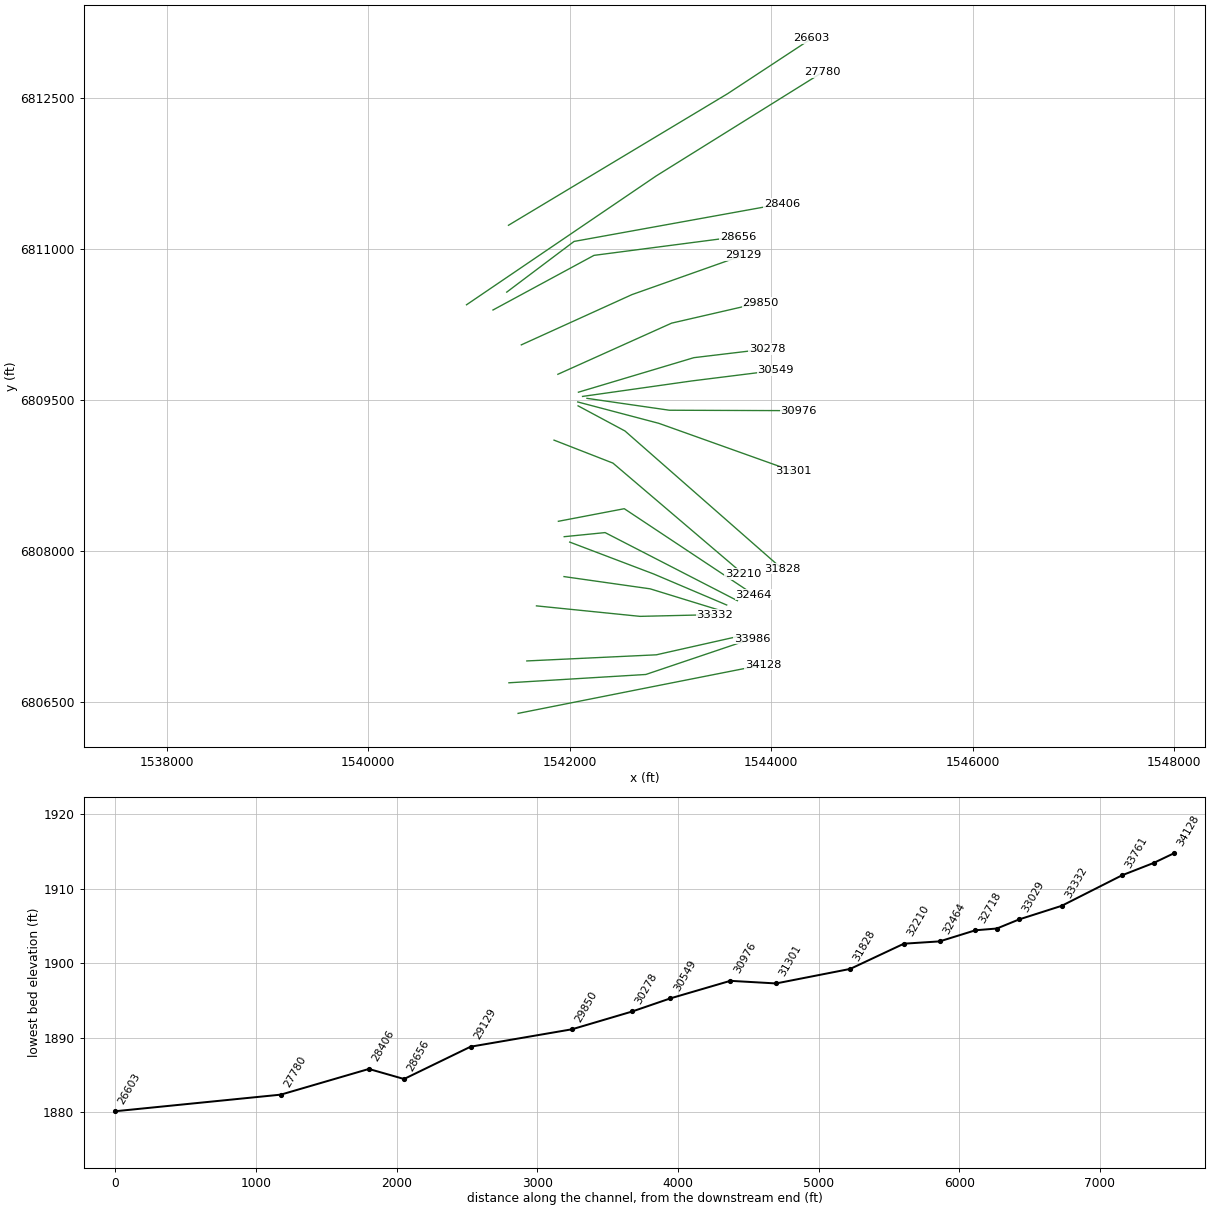
HEC-RAS study Elm 01 30.prj: Elm 01 30 Base Level Engineering

--- Elm 01 30.g01 (geometry) --- (continued)

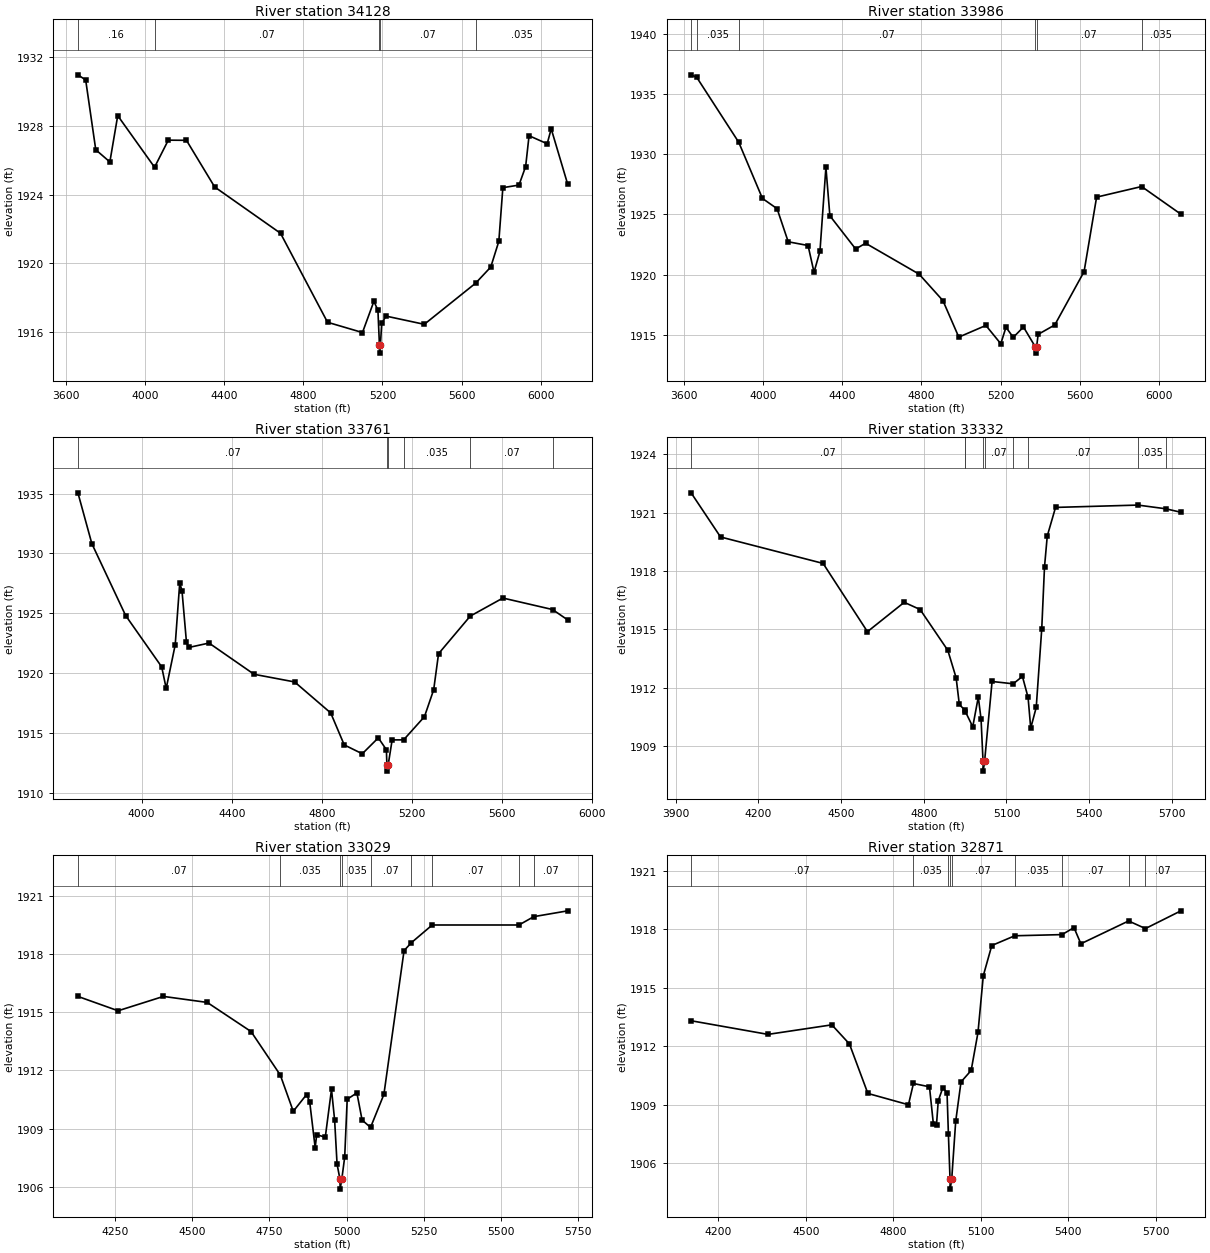
Type RM Length L Ch R = 1 ,34128   ,142,142,142
BEGIN DESCRIPTION:
Elm 01 30 34128.48
END DESCRIPTION:
XS GIS Cut Line= 3
      1541486.47      6806382.94      1542797.21      6806643.35
      1543916.98       6806864.7
#Sta/Elev= 30
  3659.4 1930.98  3698.7 1930.68  3749.7 1926.61    3821  1925.9  3860.8  1928.6
  4047.1 1925.59  4116.6 1927.17  4208.5 1927.16  4351.2 1924.44  4684.3 1921.74
  4922.1 1916.55  5098.8 1915.95  5156.6 1917.77    5177 1917.25  5184.6 1915.25
    5185 1914.75  5189.7 1915.25  5196.2 1916.48  5217.8 1916.91  5411.5 1916.43
  5671.3 1918.83  5747.8 1919.77  5788.6 1921.27    5809  1924.4  5890.5 1924.55
  5924.2 1925.63  5941.5 1927.43  6033.2 1926.96  6053.6 1927.83  6137.2 1924.59
#Mann= 5 ,-1 , 0
  3659.4     .16       0  4047.1     .07       0  5184.6     .07       0
  5189.7     .07       0  5671.3    .035       0
Bank Sta=5184.6,5189.7
XS Rating Curve= 0 ,0
Exp/Cntr=0.3,0.1

Type RM Length L Ch R = 1 ,33986   ,225,225,225
BEGIN DESCRIPTION:
Elm 01 30 33986.45
END DESCRIPTION:
XS GIS Cut Line= 3
      1541395.26      6806686.75       1542753.8      6806769.22
      1543808.52      6807125.14
#Sta/Elev= 30
  3636.9 1936.59  3665.5 1936.38  3877.8 1930.98  3997.3 1926.32  4071.2 1925.47
  4127.5 1922.72  4227.7 1922.41  4257.8 1920.19  4287.8 1921.93  4317.9 1928.91
  4337.9 1924.88  4468.2 1922.12  4518.3  1922.6  4788.8 1920.03    4909 1917.83
  4989.1  1914.8  5125.9 1915.77  5201.2 1914.25  5227.4 1915.62  5264.2 1914.78
  5315.8 1915.64  5376.4 1913.97  5376.9 1913.47  5381.9 1913.97    5390 1915.03
  5473.9 1915.81  5621.9 1920.24  5685.2 1926.43  5912.5 1927.31  6111.1 1925.01
#Mann= 6 ,-1 , 0
  3636.9     .07       0  3665.5    .035       0  3877.8     .07       0
  5376.4     .07       0  5381.9     .07       0  5912.5    .035       0
Bank Sta=5376.4,5381.9
XS Rating Curve= 0 ,0
Exp/Cntr=0.3,0.1

Type RM Length L Ch R = 1 ,33761   ,429,429,429
BEGIN DESCRIPTION:
Elm 01 30 33760.85
END DESCRIPTION:
XS GIS Cut Line= 3
      1541573.24      6806903.77      1542857.97      6806964.53
        1543726.      6807159.84
#Sta/Elev= 30
  3716.7 1935.06  3778.5 1930.82  3928.7 1924.81  4088.9 1920.52  4108.9 1918.72
  4148.9 1922.36    4169 1927.53    4179 1926.89    4199 1922.56    4209 1922.14
  4299.1 1922.51  4499.3  1919.9  4679.5 1919.26  4839.7 1916.67  4899.8    1914
  4979.9 1913.26  5051.1 1914.59    5087  1913.6  5089.3 1912.31  5089.8 1911.81
  5094.8 1912.31  5112.6 1914.42  5163.4 1914.42  5256.1 1916.36  5297.1 1918.61
  5318.7 1921.62  5459.5 1924.76  5604.6 1926.27    5825 1925.31  5892.6 1924.44
#Mann= 6 ,-1 , 0
  3716.7     .07       0  5089.3     .07       0  5094.8     .07       0
  5163.4    .035       0  5459.5     .07       0    5825    .035       0
Bank Sta=5089.3,5094.8
XS Rating Curve= 0 ,0
Exp/Cntr=0.3,0.1

Type RM Length L Ch R = 1 ,33332   ,303,303,303
BEGIN DESCRIPTION:
Elm 01 30 33331.96
END DESCRIPTION:
XS GIS Cut Line= 3
      1541668.76      6807450.64      1542697.38      6807346.48
       1543439.6      6807363.84
#Sta/Elev= 30
  3956.4 1922.02  4063.2 1919.75  4435.1 1918.39  4595.9 1914.88  4729.3 1916.39
  4786.9 1916.02  4887.4 1913.92  4917.5 1912.51  4929.1 1911.14    4948 1910.86
  4951.4 1910.76  4977.8 1909.99  4997.9 1911.52  5007.9 1910.39  5015.1 1908.21
  5015.6 1907.71  5020.7 1908.21  5047.9 1912.32  5124.5  1912.2  5157.9 1912.58
  5178.4  1911.5    5188 1909.92    5208 1910.99    5228 1915.03    5238 1918.21
    5248  1919.8    5278 1921.27  5576.8 1921.39  5677.6  1921.2  5732.7 1921.02
#Mann= 9 ,-1 , 0
  3956.4     .07       0    4948    .035       0  4951.4     .07       0
  5015.1     .07       0  5020.7     .07       0  5124.5    .035       0
  5178.4     .07       0  5576.8    .035       0  5677.6     .07       0
Bank Sta=5015.1,5020.7
XS Rating Curve= 0 ,0
Exp/Cntr=0.3,0.1

Type RM Length L Ch R = 1 ,33029   ,158,158,158
BEGIN DESCRIPTION:
Elm 01 30 33029.26
END DESCRIPTION:
XS GIS Cut Line= 3
      1541942.14      6807741.45      1542797.21      6807619.92
      1543487.32      6807407.24
#Sta/Elev= 30
  4129.9 1915.81    4260 1915.07  4406.8 1915.81  4548.6  1915.5  4690.4    1914
  4785.1 1911.76  4827.1 1909.89  4870.1 1910.75  4880.2 1910.39    4898 1908.02
    4903 1908.69  4930.7 1908.55  4950.9 1911.02    4961 1909.44  4968.9 1907.17
  4978.4 1906.38  4978.8 1905.88  4984.1 1906.38  4993.6 1907.53  5001.7 1910.51
  5033.1 1910.84  5049.9 1909.44  5077.3 1909.06  5120.5 1910.76  5185.8 1918.17
  5209.6 1918.58    5277 1919.49  5557.7 1919.49  5605.8 1919.92  5715.7 1920.22
#Mann= 9 ,-1 , 0
  4129.9     .07       0  4785.1    .035       0  4978.4    .035       0
  4984.1    .035       0  5077.3     .07       0  5209.6    .035       0
    5277     .07       0  5557.7    .035       0  5605.8     .07       0
Bank Sta=4978.4,4984.1
XS Rating Curve= 0 ,0
Exp/Cntr=0.3,0.1

Type RM Length L Ch R = 1 ,32871   ,153,153,153
BEGIN DESCRIPTION:
Elm 01 30 32871.21
END DESCRIPTION:
XS GIS Cut Line= 3
      1541998.58      6808084.33      1542831.93      6807767.49
      1543556.79      6807459.31
#Sta/Elev= 30
  4106.6  1913.3  4370.2  1912.6  4589.1 1913.09  4649.4 1912.11  4712.6 1909.57
  4851.7 1908.99  4868.8 1910.08  4923.8 1909.91  4937.2    1908  4947.9 1907.97
  4953.9  1909.2  4969.3 1909.85    4984 1909.61  4988.7 1907.48  4994.3 1905.16
  4994.7 1904.66    5000 1905.16  5013.7 1908.14  5031.9 1910.16  5066.7 1910.75
  5090.1  1912.7  5108.3 1915.61  5137.4 1917.16  5216.2 1917.66  5378.3 1917.72
  5419.2 1918.08  5442.8 1917.25  5606.4 1918.42  5664.2 1918.03  5785.8 1918.94
#Mann= 9 ,-1 , 0
  4106.6     .07       0  4868.8    .035       0  4988.7     .07       0
  4994.3     .07       0    5000     .07       0  5216.2    .035       0
  5378.3     .07       0  5606.4    .035       0  5664.2     .07       0
Bank Sta=4994.3,5000
XS Rating Curve= 0 ,0
Exp/Cntr=0.3,0.1

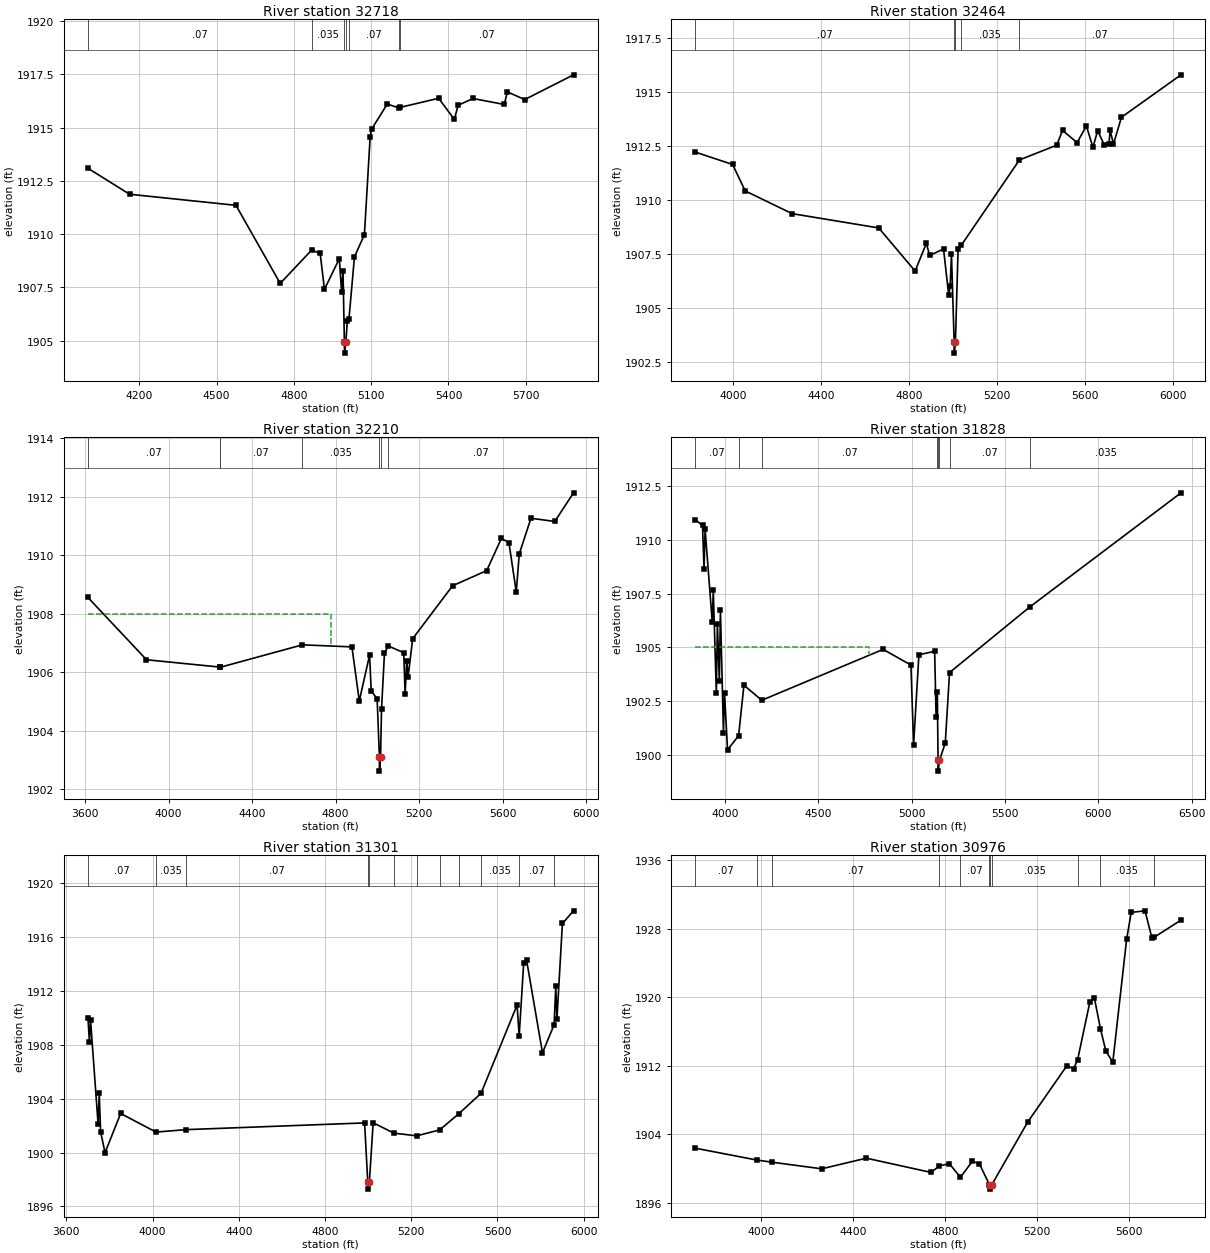
Type RM Length L Ch R = 1 ,32718   ,254,254,254
BEGIN DESCRIPTION:
Elm 01 30 32717.67
END DESCRIPTION:
XS GIS Cut Line= 3
      1541944.11      6808137.85      1542349.74      6808178.56
      1543663.38      6807502.23
#Sta/Elev= 30
  4000.4 1913.09  4162.1 1911.87  4575.1 1911.35  4746.9 1907.69  4868.8 1909.25
    4902  1909.1  4918.6 1907.41  4976.4 1908.85  4985.1  1907.3  4990.7 1908.29
    4996 1904.92  4996.5 1904.42  5001.7 1904.92  5007.3 1905.92  5013.6    1906
  5035.1 1908.93  5073.8 1909.98    5096 1914.55  5101.6 1914.92  5162.5  1916.1
  5209.5 1915.91  5211.3 1915.94    5362 1916.37  5422.9 1915.38  5437.5 1916.04
    5495 1916.36  5616.8 1916.08  5628.7 1916.67  5696.2 1916.31  5885.6 1917.47
#Mann= 7 ,-1 , 0
  4000.4     .07       0  4868.8    .035       0    4996    .035       0
  5001.7    .035       0  5013.6     .07       0  5209.5    .035       0
  5211.3     .07       0
Bank Sta=4996,5001.7
XS Rating Curve= 0 ,0
Exp/Cntr=0.3,0.1

Type RM Length L Ch R = 1 ,32464   ,254,254,254
BEGIN DESCRIPTION:
Elm 01 30 32463.05
END DESCRIPTION:
XS GIS Cut Line= 3
      1541886.27       6808290.8       1542540.2      6808415.83
       1543824.9       6807562.6
#Sta/Elev= 30
  3830.2 1912.21  3999.3 1911.64  4056.5 1910.42  4269.9 1909.37  4663.8 1908.71
  4829.1 1906.72  4880.3    1908  4895.3 1907.44  4958.4 1907.74  4981.9 1905.61
  4988.5 1906.02  4994.5 1907.49  5006.7 1903.43  5007.2 1902.93  5012.4 1903.43
  5024.6 1907.75  5039.8 1907.92  5303.5 1911.85  5472.6 1912.53  5499.7 1913.21
  5565.8 1912.65  5607.9 1913.42    5638 1912.43    5659  1913.2  5689.1 1912.55
  5710.2 1912.57  5716.2 1913.21  5731.2 1912.58  5767.3 1913.82  6038.2 1915.78
#Mann= 5 ,-1 , 0
  3830.2     .07       0  5006.7     .07       0  5012.4     .07       0
  5039.8    .035       0  5303.5     .07       0
Bank Sta=5006.7,5012.4
XS Rating Curve= 0 ,0
Exp/Cntr=0.3,0.1

Type RM Length L Ch R = 1 ,32210   ,382,382,382
BEGIN DESCRIPTION:
Elm 01 30 32209.56
END DESCRIPTION:
XS GIS Cut Line= 3
      1541843.32       6809096.8      1542427.87      6808868.67
      1543720.61       6807766.8
#Sta/Elev= 30
  3613.3 1908.56  3893.8 1906.43  4243.9 1906.18  4245.7 1906.17  4640.3 1906.94
  4877.9 1906.87  4913.1 1905.02  4962.5 1906.59  4970.2 1905.37  4998.7 1905.09
  5009.4 1903.12  5009.9 1902.62  5015.1 1903.12  5019.6 1904.73  5033.8 1906.66
  5052.7  1906.9  5126.1 1906.67  5132.7 1905.26  5140.4  1906.4  5146.9 1905.84
  5168.9 1907.15    5360 1908.96  5523.6 1909.48  5593.8 1910.58  5629.8 1910.44
  5665.2 1908.75  5679.5 1910.05  5735.5 1911.27  5849.7 1911.16  5939.4 1912.14
#Mann= 7 ,-1 , 0
  3613.3     .07       0  4243.9    .035       0  4245.7     .07       0
  4640.3    .035       0  5009.4    .035       0  5015.1    .035       0
  5052.7     .07       0
#XS Ineff= 2 , 0
       0    4778    1908               0
Permanent Ineff=
       F       F
Bank Sta=5009.4,5015.1
XS Rating Curve= 0 ,0
Exp/Cntr=0.3,0.1

Type RM Length L Ch R = 1 ,31828   ,527,527,527
BEGIN DESCRIPTION:
Elm 01 30 31691.81
END DESCRIPTION:
XS GIS Cut Line= 3
      1542081.97      6809437.36      1542547.19      6809187.78
      1544105.29      6807819.58
#Sta/Elev= 30
  3841.7 1910.93  3879.6 1910.67  3887.9 1908.64  3893.6 1910.49  3931.7 1906.19
  3937.4 1907.65  3953.7 1902.85  3959.3 1906.09  3969.9 1903.43  3975.6 1906.73
  3991.8 1901.02  3997.5 1902.88  4013.8 1900.22    4073 1900.88  4101.5 1903.23
  4197.2 1902.53  4847.3  1904.9  4996.3 1904.17  5010.5 1900.45    5039 1904.65
  5123.4 1904.81    5131 1901.75  5137.7 1902.91  5141.6 1899.73  5142.1 1899.23
  5148.9 1899.73  5180.3 1900.54  5203.1 1903.82  5633.7 1906.88  6443.2 1912.19
#Mann= 8 ,-1 , 0
  3841.7     .07       0    4073    .035       0  4197.2     .07       0
  5137.7    .035       0  5141.6     .07       0  5148.9    .035       0
  5203.1     .07       0  5633.7    .035       0
#XS Ineff= 2 , 0
       0    4770    1905               0
Permanent Ineff=
       F       F
Bank Sta=5141.6,5148.9
XS Rating Curve= 0 ,0
Exp/Cntr=0.3,0.1

Type RM Length L Ch R = 1 ,31301   ,325,325,325
BEGIN DESCRIPTION:
Elm 01 30 31301.1
END DESCRIPTION:
XS GIS Cut Line= 3
      1542078.32      6809476.03       1542883.6      6809263.63
      1544220.19      6808786.28
#Sta/Elev= 30
  3700.5 1910.01  3707.3 1908.23  3712.5 1909.85  3747.6 1902.11  3752.8 1904.39
  3759.1 1901.55  3779.8 1899.99  3852.2  1902.9  4016.1 1901.52  4154.5  1901.7
  4983.6  1902.2  4998.4 1897.78  4998.9 1897.28  5005.7 1897.78  5023.3 1902.21
  5119.4 1901.44  5225.6 1901.24  5331.7 1901.68  5419.7 1902.87  5523.7  1904.4
  5690.8 1910.96  5700.6 1908.67  5721.6 1914.09  5734.7 1914.31  5808.7 1907.41
  5862.6  1909.5  5870.3 1912.34  5875.6 1909.89  5901.1 1917.02  5952.6 1917.96
#Mann= 12 ,-1 , 0
  3700.5     .07       0  4016.1    .035       0  4154.5     .07       0
  4998.4     .07       0  5005.7     .07       0  5119.4    .035       0
  5225.6     .07       0  5331.7    .035       0  5419.7     .07       0
  5523.7    .035       0  5700.6     .07       0  5862.6    .035       0
Bank Sta=4998.4,5005.7
XS Rating Curve= 0 ,0
Exp/Cntr=0.3,0.1

Type RM Length L Ch R = 1 ,30976   ,427,427,427
BEGIN DESCRIPTION:
Elm 01 30 30975.69
END DESCRIPTION:
XS GIS Cut Line= 3
      1542170.18      6809511.94      1542987.76      6809393.84
      1544271.29       6809389.5
#Sta/Elev= 30
  3715.9  1902.4    3983 1901.02  4048.5 1900.77  4264.7    1900  4458.3 1901.24
  4739.2 1899.58  4776.1 1900.34  4819.2  1900.6    4867 1899.01  4919.2 1900.87
  4949.2  1900.6    4993 1898.16  4995.2 1898.13  4995.7 1897.63  5003.3 1898.13
  5159.2 1905.44  5329.2    1912  5359.2 1911.69  5376.5 1912.73  5429.2 1919.41
  5449.2 1919.92  5475.5 1916.33  5499.2 1913.71  5529.2 1912.44  5589.2 1926.75
  5609.2  1929.9  5669.2 1930.08  5699.2 1926.91  5709.7 1927.01  5825.5    1929
#Mann= 11 ,-1 , 0
  3715.9     .07       0    3983    .035       0  4048.5     .07       0
  4776.1    .035       0    4867     .07       0    4993    .035       0
  4995.2    .035       0  5003.3    .035       0  5376.5     .07       0
  5475.5    .035       0  5709.7     .07       0
Bank Sta=4995.2,5003.3
XS Rating Curve= 0 ,0
Exp/Cntr=0.3,0.1

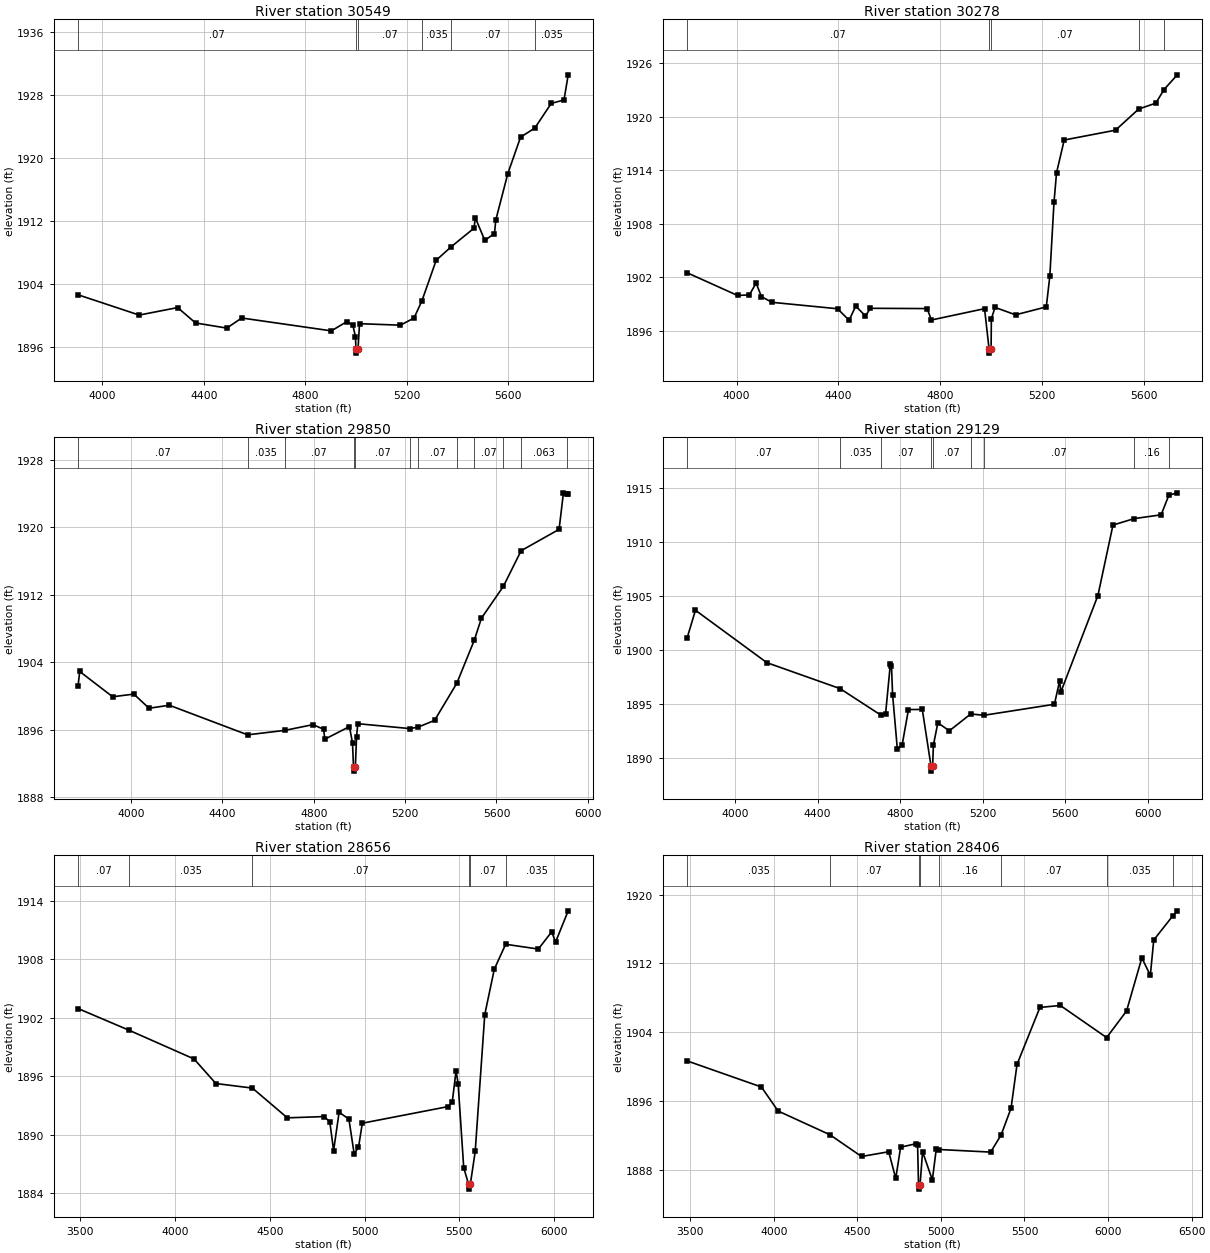
Type RM Length L Ch R = 1 ,30549   ,271,271,271
BEGIN DESCRIPTION:
Elm 01 30 30548.65
END DESCRIPTION:
XS GIS Cut Line= 3
      1542126.26      6809531.08      1543209.12      6809684.64
      1544041.25      6809788.65
#Sta/Elev= 30
  3903.7 1902.66  4144.8 1900.09  4296.3 1901.04    4367 1899.09  4490.2 1898.44
  4548.8 1899.72  4902.3 1898.09  4962.9 1899.25  4986.9 1898.84  4997.4 1897.35
  4999.3 1895.77  4999.8 1895.27  5007.4 1895.77  5013.4    1899  5174.6 1898.81
  5228.1 1899.71  5259.1 1901.87  5315.7 1907.04  5375.5 1908.76  5464.9  1911.1
  5469.9 1912.42  5507.2 1909.55  5545.5 1910.42  5550.5 1912.12  5597.9    1918
  5648.3 1922.63  5704.3 1923.77  5769.2  1926.9  5819.6 1927.34    5836 1930.52
#Mann= 6 ,-1 , 0
  3903.7     .07       0  4999.3     .07       0  5007.4     .07       0
  5259.1    .035       0  5375.5     .07       0  5704.3    .035       0
Bank Sta=4999.3,5007.4
XS Rating Curve= 0 ,0
Exp/Cntr=0.3,0.1

Type RM Length L Ch R = 1 ,30278   ,428,428,428
BEGIN DESCRIPTION:
Elm 01 30 30277.65
END DESCRIPTION:
XS GIS Cut Line= 3
      1542085.39      6809573.04      1543231.24      6809915.92
      1543956.11      6810002.73
#Sta/Elev= 30
    3806 1902.51  4003.9 1899.97  4050.5 1900.03    4077 1901.36  4097.9 1899.83
  4139.6  1899.2  4397.1 1898.48  4442.3 1897.19  4468.5 1898.78  4506.8 1897.67
  4525.8 1898.53    4749  1898.5  4765.9 1897.22  4974.7 1898.49  4992.3 1894.01
  4992.8 1893.51  5000.4 1894.01  5001.4 1897.36  5015.9 1898.63  5096.5  1897.8
  5217.3 1898.69  5231.1  1902.1  5247.6 1910.41  5257.6 1913.72  5287.8 1917.38
  5489.3 1918.48  5580.5 1920.85  5647.8 1921.51  5679.9 1923.03  5732.1 1924.68
#Mann= 5 ,-1 , 0
    3806     .07       0  4992.3     .07       0  5000.4     .07       0
  5580.5    .035       0  5679.9    .063       0
Bank Sta=4992.3,5000.4
XS Rating Curve= 0 ,0
Exp/Cntr=0.3,0.1

Type RM Length L Ch R = 1 ,29850   ,721,721,721
BEGIN DESCRIPTION:
Elm 01 30 29850.42
END DESCRIPTION:
XS GIS Cut Line= 3
      1541881.39      6809750.99      1543009.88      6810258.81
       1543895.3       6810462.8
#Sta/Elev= 30
  3767.9  1901.2  3775.1 1902.93  3919.5 1899.93  4012.1 1900.25  4078.9 1898.57
  4167.4 1898.93  4510.4 1895.42  4673.5 1895.95  4796.7 1896.63    4843 1896.08
  4848.5  1894.9  4956.2  1896.4  4969.7 1894.44    4974 1891.62  4974.5 1891.12
  4982.1 1891.62  4987.4 1895.22  4992.9 1896.74  5221.4 1896.16  5257.2 1896.34
  5328.8 1897.13  5426.3 1901.53  5503.1 1906.65    5534 1909.24  5630.3 1913.02
  5707.9 1917.24  5874.1 1919.77  5893.2  1924.1  5909.8    1924    5914 1924.01
#Mann= 12 ,-1 , 0
  3767.9     .07       0  4510.4    .035       0  4673.5     .07       0
    4974     .07       0  4982.1     .07       0  5221.4    .035       0
  5257.2     .07       0  5426.3    .035       0  5503.1     .07       0
  5630.3     .16       0  5707.9    .063       0  5909.8     .07       0
Bank Sta=4974,4982.1
XS Rating Curve= 0 ,0
Exp/Cntr=0.3,0.1

Type RM Length L Ch R = 1 ,29129   ,473,473,473
BEGIN DESCRIPTION:
Elm 01 30 29553.74
END DESCRIPTION:
XS GIS Cut Line= 3
      1541518.41      6810043.14      1542616.47      6810542.26
      1543718.93      6810932.89
#Sta/Elev= 30
  3767.4 1901.14  3807.6  1903.7  4153.7 1898.84  4508.8 1896.43  4707.7 1893.96
  4729.3 1894.11  4752.3 1898.71  4757.8 1898.55  4763.3 1895.84  4786.4 1890.79
  4809.4  1891.2  4840.1 1894.49  4907.2  1894.5  4949.2 1889.28  4949.7 1888.78
  4957.4 1889.28    4961  1891.2  4982.6 1893.26  5038.3 1892.52  5141.8 1894.08
  5206.3 1893.96  5547.5 1894.98    5573 1897.16  5578.3  1896.1  5758.3 1905.06
  5831.4  1911.6  5934.4  1912.2  6064.8 1912.55  6102.3 1914.37  6143.2 1914.59
#Mann= 9 ,-1 , 0
  3767.4     .07       0  4508.8    .035       0  4707.7     .07       0
  4949.2     .07       0  4957.4     .07       0  5141.8    .035       0
  5206.3     .07       0  5934.4     .16       0  6102.3    .035       0
Bank Sta=4949.2,4957.4
XS Rating Curve= 0 ,0
Exp/Cntr=0.3,0.1

Type RM Length L Ch R = 1 ,28656   ,250,250,250
BEGIN DESCRIPTION:
Elm 01 30 28909.64
END DESCRIPTION:
XS GIS Cut Line= 3
      1541237.11      6810389.46      1542239.75      6810932.01
      1543671.03      6811118.51
#Sta/Elev= 30
  3489.8 1902.96  3757.9 1900.74  4101.1 1897.79  4216.2 1895.27    4409  1894.8
  4592.9 1891.75  4786.4 1891.88  4816.6 1891.36  4836.8 1888.39  4865.8 1892.33
  4917.5 1891.61  4944.9 1888.09  4967.9 1888.71  4988.1  1891.2  5441.9 1892.91
    5462 1893.35  5482.2 1896.57  5493.1 1895.25  5522.6 1886.64  5548.2 1884.94
  5548.7 1884.44  5557.5 1884.94  5583.1  1888.3  5633.5 1902.34  5683.9    1907
  5743.5 1909.55  5915.9 1909.06  5986.4 1910.83  6006.6 1909.77  6073.2 1912.98
#Mann= 6 ,-1 , 0
  3489.8     .07       0  3757.9    .035       0    4409     .07       0
  5548.2     .07       0  5557.5     .07       0  5743.5    .035       0
Bank Sta=5548.2,5557.5
XS Rating Curve= 0 ,0
Exp/Cntr=0.3,0.1

Type RM Length L Ch R = 1 ,28406   ,626,626,626
BEGIN DESCRIPTION:
Elm 01 30 28405.92
END DESCRIPTION:
XS GIS Cut Line= 3
      1541373.59      6810566.96        1542042.      6811070.44
      1544103.66      6811443.71
#Sta/Elev= 30
  3482.2 1900.68  3926.4 1897.65  4026.3 1894.86  4335.9 1892.11  4525.3 1889.58
  4687.9 1890.13    4730 1887.03  4759.1 1890.66  4850.5 1891.06  4860.7 1890.93
  4866.2 1886.29  4866.7 1885.79  4875.5 1886.29  4890.4 1890.14  4948.9 1886.86
  4972.5 1890.45  4991.4 1890.39  5297.7 1890.09  5360.3 1892.08  5419.6 1895.18
  5455.6 1900.28  5592.4 1906.89  5714.3 1907.12  5991.5 1903.39  6110.7 1906.48
  6202.1 1912.64    6253 1910.62  6273.3 1914.72  6386.2  1917.5  6414.2 1918.11
#Mann= 8 ,-1 , 0
  3482.2    .035       0  4335.9     .07       0  4866.2     .07       0
  4875.5     .07       0  4991.4     .16       0  5360.3     .07       0
  5991.5    .035       0  6386.2     .07       0
Bank Sta=4866.2,4875.5
XS Rating Curve= 0 ,0
Exp/Cntr=0.3,0.1

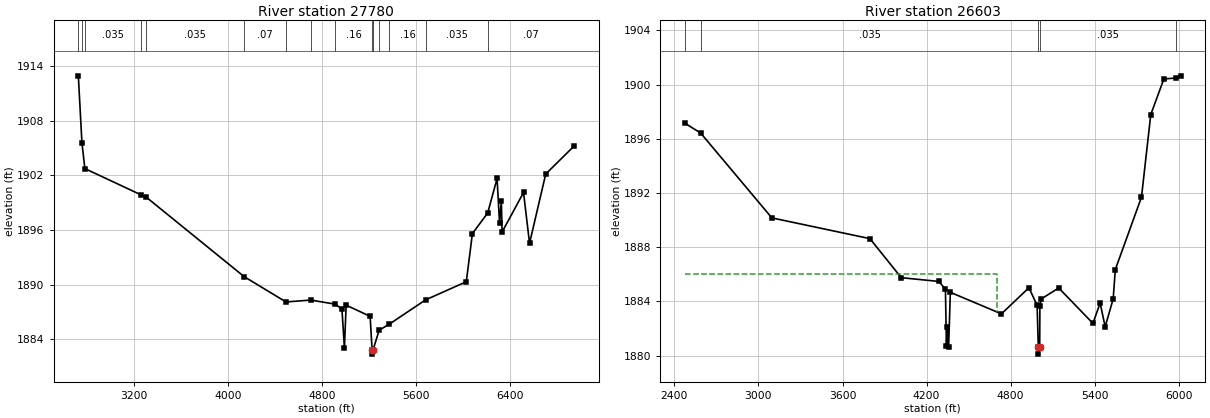
Type RM Length L Ch R = 1 ,27780   ,1177,1177,1177
BEGIN DESCRIPTION:
Elm 01 30 27780.25
END DESCRIPTION:
XS GIS Cut Line= 3
      1540974.31      6810441.11      1542857.97      6811721.48
      1544507.27      6812750.12
#Sta/Elev= 30
    2725 1912.97  2755.7 1905.59  2780.7 1902.76  3260.4 1899.86  3300.9 1899.64
  4136.6 1890.87  4493.2 1888.08  4703.1 1888.29  4912.4 1887.84  4969.3  1887.3
  4990.3 1883.03  5005.2 1887.73  5209.4  1886.5  5225.8 1882.84  5226.3 1882.34
  5235.3 1882.84  5285.8 1884.97  5372.7 1885.64  5681.3 1888.31  6028.1 1890.31
    6080 1895.61  6210.2 1897.87    6290 1901.67  6311.3 1896.77  6326.6 1899.23
  6332.5 1895.77  6515.4 1900.13  6566.6 1894.54  6704.2 1902.16  6946.4 1905.25
#Mann= 15 ,-1 , 0
    2725    .035       0  2755.7    .063       0  2780.7    .035       0
  3260.4    .063       0  3300.9    .035       0  4136.6     .07       0
  4493.2    .035       0  4703.1     .07       0  4912.4     .16       0
  5225.8     .07       0  5235.3     .16       0  5285.8    .035       0
  5372.7     .16       0  5681.3    .035       0  6210.2     .07       0
Bank Sta=5225.8,5235.3
XS Rating Curve= 0 ,0
Exp/Cntr=0.3,0.1

Type RM Length L Ch R = 1 ,26603   ,219,219,219
BEGIN DESCRIPTION:
Elm 01 30 26602.76
END DESCRIPTION:
XS GIS Cut Line= 3
      1541390.93      6811231.01      1543565.44      6812537.45
      1544401.57      6813087.65
#Sta/Elev= 30
  2474.8 1897.15  2587.8 1896.42    3096 1890.16  3795.5 1888.63  4019.5 1885.75
  4289.1 1885.47  4334.4 1884.88  4341.5 1880.71  4347.3 1882.09  4357.1 1880.61
  4369.4 1884.67    4734 1883.08  4930.3 1885.01  4988.5 1883.71  4997.2 1880.61
  4997.7 1880.11    5007 1880.61  5008.4 1883.68  5019.4 1884.19  5142.7 1884.99
  5386.8 1882.38  5438.1 1883.88  5474.2 1882.13  5531.4 1884.19  5546.5 1886.35
  5733.2 1891.69  5799.5 1897.78  5892.9 1900.41  5981.4 1900.48  6012.5 1900.64
#Mann= 5 ,-1 , 0
  2474.8     .07       0  2587.8    .035       0  4997.2    .035       0
    5007    .035       0  5981.4    .063       0
#XS Ineff= 2 , 0
       0    4700    1886               0
Permanent Ineff=
       F       F
Bank Sta=4997.2,5007
XS Rating Curve= 0 ,0
Exp/Cntr=0.3,0.1