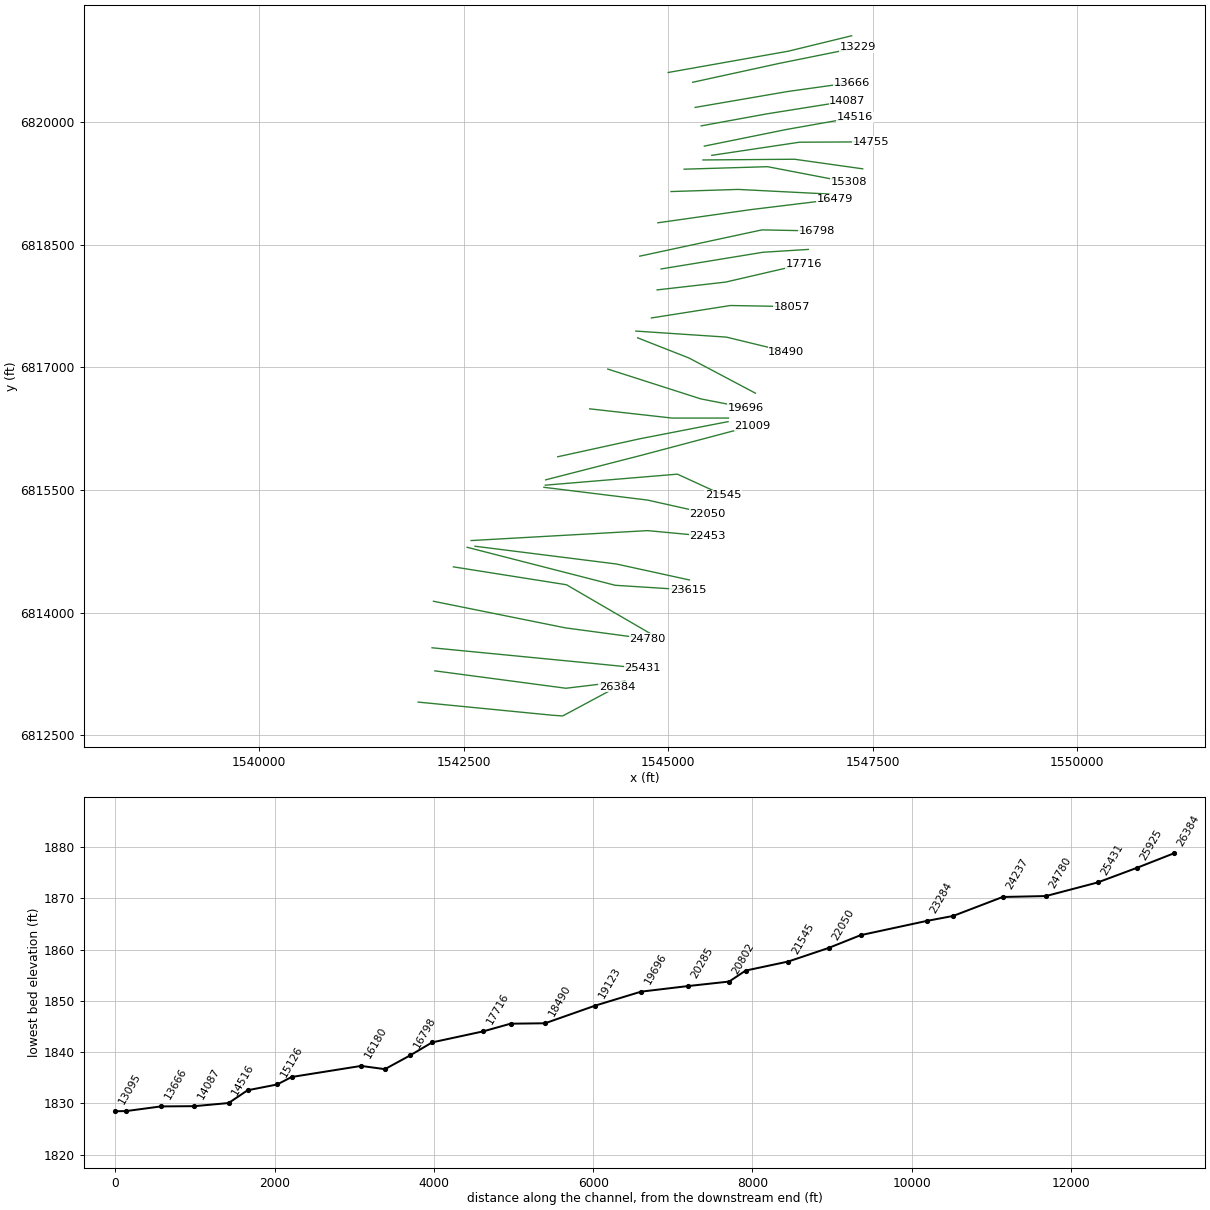
HEC-RAS study Elm 01 30.prj: Elm 01 30 Base Level Engineering

--- Elm 01 30.g01 (geometry) --- (continued)

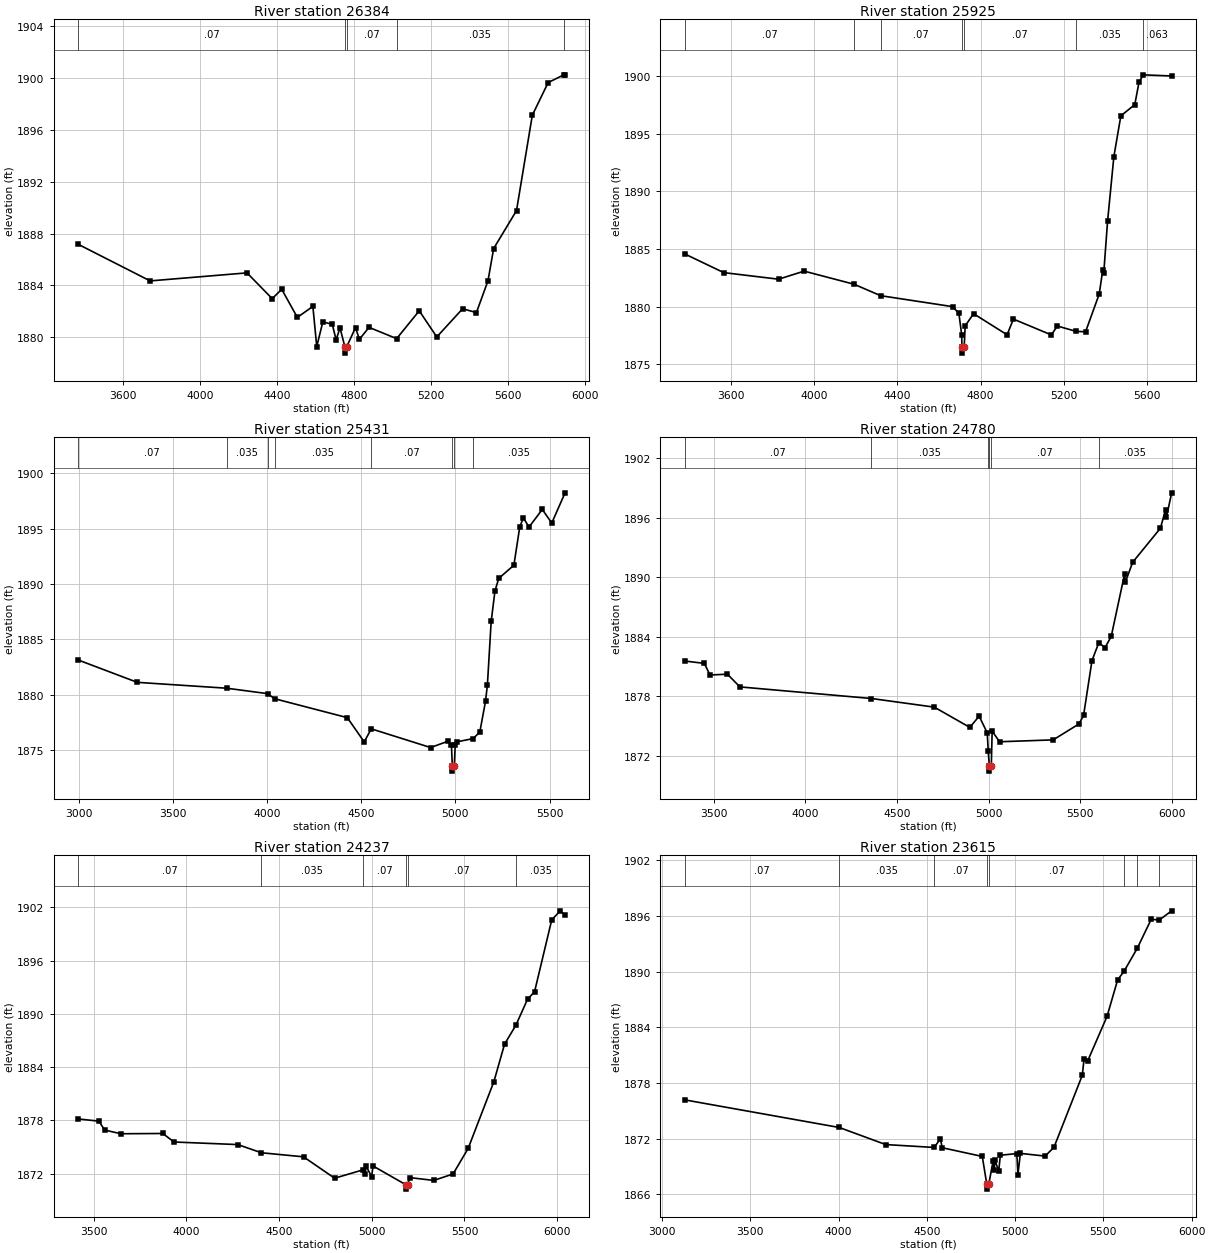
Type RM Length L Ch R = 1 ,26384   ,459,459,459
BEGIN DESCRIPTION:
Elm 01 30 26383.92
END DESCRIPTION:
XS GIS Cut Line= 4
      1541942.17      6812906.38       1543582.8      6812745.78
      1543708.67       6812737.1      1544371.35      6813092.27
#Sta/Elev= 30
  3368.3 1887.18  3742.9 1884.34  4245.3 1884.96  4375.9 1882.97  4425.3 1883.69
  4506.5 1881.52  4586.9 1882.37    4607 1879.27  4638.5 1881.17  4687.4 1880.99
  4707.5 1879.79  4727.6 1880.71  4752.8 1879.26  4753.3 1878.76  4762.6 1879.26
    4808 1880.73  4828.1 1879.83  4878.3 1880.75  5021.4 1879.88  5138.6 1882.03
  5229.5 1880.01  5363.6 1882.19    5435 1881.89  5495.1 1884.35  5524.5 1886.84
    5643 1889.77    5725 1897.14  5807.1 1899.66  5888.3 1900.26  5894.8 1900.21
#Mann= 5 ,-1 , 0
  3368.3     .07       0  4752.8     .07       0  4762.6     .07       0
  5021.4    .035       0  5888.3    .063       0
Bank Sta=4752.8,4762.6
XS Rating Curve= 0 ,0
Exp/Cntr=0.3,0.1

Type RM Length L Ch R = 1 ,25925   ,494,494,494
BEGIN DESCRIPTION:
Elm 01 30 25924.56
END DESCRIPTION:
XS GIS Cut Line= 3
      1542146.16      6813288.32      1543747.73      6813075.65
      1544471.23      6813162.29
#Sta/Elev= 30
  3375.4 1884.57  3564.3 1882.94  3828.2 1882.37  3950.9 1883.07  4191.8 1881.93
  4319.2 1880.94  4665.5 1879.99  4695.7 1879.41  4709.1 1877.56  4710.6 1876.46
  4711.1 1875.96  4721.2 1876.46    4726 1878.32  4766.3 1879.38  4927.7 1877.55
    4958 1878.91  5140.7 1877.54  5169.6 1878.31  5259.3 1877.85  5305.3 1877.81
    5371 1881.08  5387.7 1883.13  5392.7 1882.88  5411.3 1887.41  5441.5    1893
  5475.1 1896.53  5542.2 1897.51  5562.4 1899.44  5582.6 1900.09  5719.7 1899.99
#Mann= 7 ,-1 , 0
  3375.4     .07       0  4191.8    .035       0  4319.2     .07       0
  4710.6     .07       0  4721.2     .07       0  5259.3    .035       0
  5582.6    .063       0
Bank Sta=4710.6,4721.2
XS Rating Curve= 0 ,0
Exp/Cntr=0.3,0.1

Type RM Length L Ch R = 1 ,25431   ,651,651,651
BEGIN DESCRIPTION:
Elm 01 30 25430.71
END DESCRIPTION:
XS GIS Cut Line= 3
      1542111.43      6813570.44      1544120.99      6813375.13
      1544685.24       6813318.7
#Sta/Elev= 30
  2996.4 1883.15  3311.5 1881.12  3786.1 1880.59  4003.3  1880.1  4040.7 1879.64
  4426.7 1877.93  4516.3 1875.74  4553.7 1876.92  4868.8 1875.23  4959.2 1875.79
  4979.3 1875.46    4984  1873.6  4984.5  1873.1  4994.6  1873.6  4999.4 1875.46
  5009.4 1875.75  5094.6 1876.04    5130 1876.63  5160.2 1879.41  5170.2 1880.88
  5190.3 1886.62  5210.4 1889.38  5230.5 1890.51  5310.9  1891.7  5342.2 1895.18
  5361.2 1895.97  5391.3 1895.15  5461.7 1896.74  5511.9 1895.51  5582.5 1898.24
#Mann= 8 ,-1 , 0
  2996.4     .07       0  3786.1    .035       0  4003.3     .07       0
  4040.7    .035       0  4553.7     .07       0    4984     .07       0
  4994.6     .07       0  5094.6    .035       0
Bank Sta=4984,4994.6
XS Rating Curve= 0 ,0
Exp/Cntr=0.3,0.1

Type RM Length L Ch R = 1 ,24780   ,543,543,543
BEGIN DESCRIPTION:
Elm 01 30 24780.05
END DESCRIPTION:
XS GIS Cut Line= 3
      1542128.84      6814139.01      1543743.39      6813813.49
      1544745.97      6813678.95
#Sta/Elev= 30
    3341 1881.54  3449.3  1881.3  3479.9 1880.13  3575.3 1880.21  3643.1 1878.93
  4361.2 1877.76    4704 1876.89  4897.9 1874.85  4948.9 1875.98  4993.2 1874.29
  4998.5 1872.44  5004.5 1870.94    5005 1870.44  5015.2 1870.94  5019.9 1874.47
  5060.3  1873.4  5352.9 1873.59  5494.1  1875.2  5518.7 1876.05  5564.8 1881.59
  5602.4  1883.4  5635.4 1882.88  5669.6 1884.01  5742.5 1890.29  5747.5 1889.52
  5786.7 1891.49  5938.1 1894.92  5966.2 1896.78  5971.3 1896.08  5999.6 1898.49
#Mann= 6 ,-1 , 0
    3341     .07       0  4361.2    .035       0  4998.5     .07       0
  5004.5     .07       0  5015.2     .07       0  5602.4    .035       0
Bank Sta=5004.5,5015.2
XS Rating Curve= 0 ,0
Exp/Cntr=0.3,0.1

Type RM Length L Ch R = 1 ,24237   ,622,622,622
BEGIN DESCRIPTION:
Elm 01 30 24237.27
END DESCRIPTION:
XS GIS Cut Line= 3
      1542372.73      6814559.64      1543754.69      6814340.89
      1544817.06      6813722.91
#Sta/Elev= 30
  3414.6 1878.17  3528.3 1877.92  3558.6 1876.92  3646.8  1876.5  3872.5 1876.53
  3933.2 1875.57  4277.5 1875.28  4403.9 1874.36  4631.8  1873.9  4799.6 1871.49
  4952.2 1872.43  4963.7 1871.92  4969.5 1872.85  4999.2 1871.66  5006.7 1872.87
  5183.4 1870.76  5183.9 1870.26  5194.1 1870.76  5204.5 1871.56  5334.7 1871.24
  5438.8 1871.97  5519.8 1874.84  5658.6 1882.36  5716.5  1886.6  5777.2 1888.72
  5840.9 1891.68  5878.1 1892.49    5971 1900.61  6017.1 1901.62  6042.8 1901.12
#Mann= 6 ,-1 , 0
  3414.6     .07       0  4403.9    .035       0  4952.2     .07       0
  5183.4     .07       0  5194.1     .07       0  5777.2    .035       0
Bank Sta=5183.4,5194.1
XS Rating Curve= 0 ,0
Exp/Cntr=0.3,0.1

Type RM Length L Ch R = 1 ,23615   ,331,331,331
BEGIN DESCRIPTION:
Elm 01 30 23615.25
END DESCRIPTION:
XS GIS Cut Line= 3
      1542541.08      6814798.75      1544351.03      6814334.33
      1545240.36      6814277.93
#Sta/Elev= 30
  3127.1 1876.18  4003.8  1873.2  4266.8 1871.36  4541.9 1871.05  4576.5 1871.99
  4586.8 1871.02  4813.9 1870.08  4839.7 1867.06  4840.2 1866.56  4850.5 1867.06
  4875.5 1869.64  4880.7  1868.6  4886.2 1869.66  4906.9 1868.49  4916.3 1870.21
  5009.7 1870.39  5015.7 1868.11  5029.7 1870.41  5169.8 1870.12  5220.1 1871.07
  5380.4 1878.82  5390.4 1880.57  5410.5 1880.35  5520.7 1885.17  5580.8 1889.11
  5617.1 1890.03  5692.5 1892.53  5771.2 1895.64  5815.8 1895.54  5886.8 1896.54
#Mann= 8 ,-1 , 0
  3127.1     .07       0  4003.8    .035       0  4541.9     .07       0
  4839.7     .07       0  4850.5     .07       0  5617.1    .035       0
  5692.5     .07       0  5815.8    .035       0
Bank Sta=4839.7,4850.5
XS Rating Curve= 0 ,0
Exp/Cntr=0.3,0.1

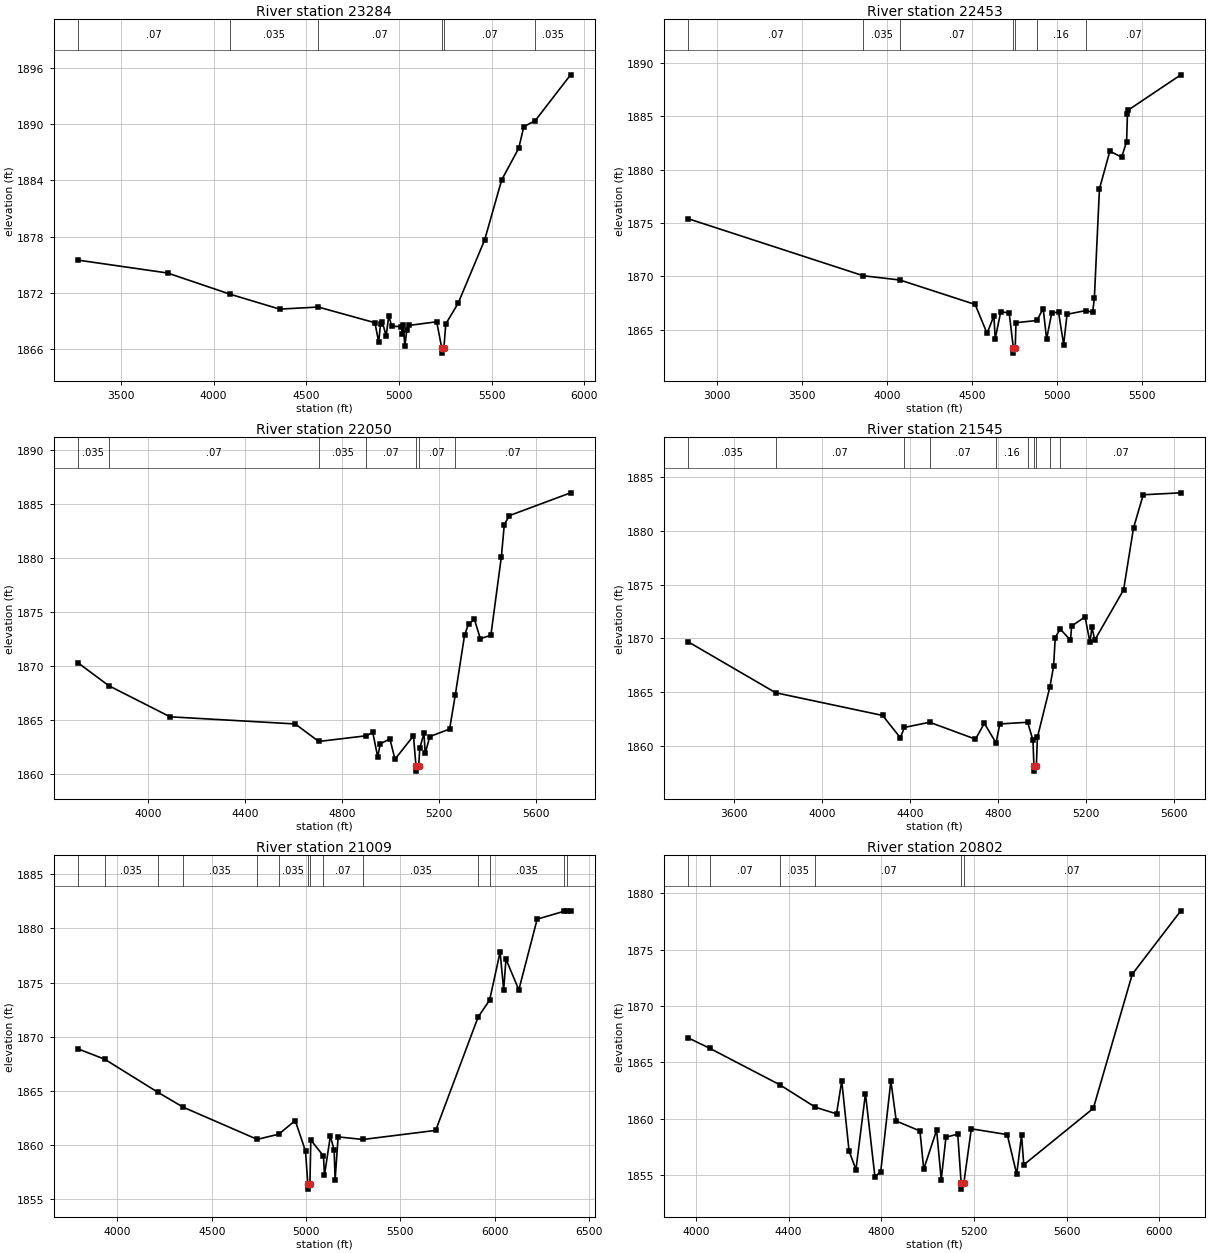
Type RM Length L Ch R = 1 ,23284   ,831,831,831
BEGIN DESCRIPTION:
Elm 01 30 23283.54
END DESCRIPTION:
XS GIS Cut Line= 3
      1542636.64      6814811.75      1544364.05      6814594.74
      1545258.18      6814399.42
#Sta/Elev= 30
  3269.6  1875.5  3751.7 1874.13  4090.7 1871.86  4356.4 1870.28  4564.9  1870.5
  4870.4 1868.83  4890.6 1866.77  4900.7 1868.68  4910.8 1868.87  4930.9 1867.42
  4945.2 1869.57  4961.2 1868.45  5013.6 1868.42  5017.7 1867.64  5022.8  1868.6
    5032 1866.33  5042.3 1868.08  5052.5 1868.54  5203.6 1868.93  5231.3 1866.09
  5231.8 1865.59  5242.1 1866.09  5252.6  1868.7  5318.6 1870.88  5461.9 1877.63
  5554.1 1884.05  5646.2 1887.43  5673.3 1889.72  5735.6 1890.38  5925.8 1895.25
#Mann= 6 ,-1 , 0
  3269.6     .07       0  4090.7    .035       0  4564.9     .07       0
  5231.3     .07       0  5242.1     .07       0  5735.6    .035       0
Bank Sta=5231.3,5242.1
XS Rating Curve= 0 ,0
Exp/Cntr=0.3,0.1

Type RM Length L Ch R = 1 ,22453   ,403,403,403
BEGIN DESCRIPTION:
Elm 01 30 22453.33
END DESCRIPTION:
XS GIS Cut Line= 3
      1542588.84       6814881.2      1544745.99      6815002.73
      1545481.87      6814933.47
#Sta/Elev= 30
  2829.7  1875.4  3859.8 1870.06  4075.9 1869.66  4518.5 1867.37  4588.6 1864.66
  4628.7 1866.31  4636.6 1864.16  4668.8 1866.67  4718.8 1866.59  4743.3 1863.31
  4743.8 1862.81  4754.4 1863.31  4758.9 1865.66  4881.9 1865.87  4919.2 1866.99
  4939.2 1864.12  4969.2 1866.56  5009.4 1866.67  5039.5 1863.61  5059.6 1866.45
  5170.4  1866.8  5210.2 1866.63  5220.3 1867.93  5250.4  1878.2  5311.6 1881.74
    5381 1881.17  5410.2 1882.63  5415.2 1885.19  5421.2  1885.6  5729.4 1888.89
#Mann= 7 ,-1 , 0
  2829.7     .07       0  3859.8    .035       0  4075.9     .07       0
  4743.3     .07       0  4754.4     .07       0  4881.9     .16       0
  5170.4     .07       0
Bank Sta=4743.3,4754.4
XS Rating Curve= 0 ,0
Exp/Cntr=0.3,0.1

Type RM Length L Ch R = 1 ,22050   ,505,505,505
BEGIN DESCRIPTION:
Elm 01 30 22049.87
END DESCRIPTION:
XS GIS Cut Line= 3
      1543478.67      6815532.24      1544745.99      6815375.99
      1545481.91      6815211.49
#Sta/Elev= 30
  3712.1 1870.31    3838 1868.21  4091.3 1865.33  4607.5 1864.67  4704.3 1863.05
  4901.1 1863.58  4927.1 1863.89  4947.7 1861.62  4957.8 1862.83  4997.9 1863.29
  5018.7 1861.41    5095 1863.57  5105.4 1860.81  5105.9 1860.31  5116.6 1860.81
  5121.2 1862.44  5138.4  1863.8  5143.5 1861.95  5162.2  1863.5  5244.2  1864.2
  5267.8 1867.38  5305.7 1872.86  5322.3 1873.93  5346.6 1874.33  5370.9 1872.55
  5414.3 1872.87  5457.7 1880.13  5469.6 1883.07  5490.1 1883.92  5743.1 1886.03
#Mann= 7 ,-1 , 0
  3712.1    .035       0    3838     .07       0  4704.3    .035       0
  4901.1     .07       0  5105.4     .07       0  5116.6     .07       0
  5267.8     .07       0
Bank Sta=5105.4,5116.6
XS Rating Curve= 0 ,0
Exp/Cntr=0.3,0.1

Type RM Length L Ch R = 1 ,21545   ,536,536,536
BEGIN DESCRIPTION:
Elm 01 30 21545.11
END DESCRIPTION:
XS GIS Cut Line= 3
      1543496.02      6815558.29      1545110.58      6815692.83
      1545670.26      6815436.85
#Sta/Elev= 30
  3394.1 1869.67  3790.4 1864.95  4276.1 1862.84  4356.4 1860.77  4375.1 1861.73
  4489.3 1862.21  4697.6 1860.64  4737.7 1862.11  4790.9 1860.29    4808 1862.05
  4934.4 1862.21  4958.5 1860.54  4962.9 1858.17  4963.4 1857.67  4974.1 1858.17
  4978.6  1860.8  5035.7 1865.52  5052.1 1867.41  5059.8 1870.07  5081.8 1870.88
  5128.8 1869.83  5134.3 1871.15  5195.1    1872  5217.1 1869.64  5226.4 1871.03
    5239 1869.84    5370 1874.51    5415 1880.25    5459 1883.34  5629.7 1883.52
#Mann= 10 ,-1 , 0
  3394.1    .035       0  3790.4     .07       0  4375.1    .035       0
  4489.3     .07       0  4790.9     .16       0  4934.4     .07       0
  4962.9     .07       0  4974.1     .07       0  5035.7     .16       0
  5081.8     .07       0
Bank Sta=4962.9,4974.1
XS Rating Curve= 0 ,0
Exp/Cntr=0.3,0.1

Type RM Length L Ch R = 1 ,21009   ,207,207,207
BEGIN DESCRIPTION:
Elm 01 30 21009.04
END DESCRIPTION:
XS GIS Cut Line= 3
      1543500.32      6815623.39      1544667.87      6815922.87
      1546026.18      6816283.06
#Sta/Elev= 30
  3792.1 1868.86  3932.8 1867.91  4214.1 1864.86  4348.3 1863.48  4741.4  1860.5
  4855.5 1860.98  4942.9 1862.24  4997.4 1859.42  5009.6  1856.4  5010.1  1855.9
  5020.8  1856.4  5025.5 1860.44  5092.7 1858.96  5097.9 1857.18    5129  1860.8
  5149.2 1859.51  5154.4 1856.76  5170.3 1860.73  5301.8 1860.49  5687.6 1861.33
  5912.5 1871.81  5973.4 1873.37    6029 1877.82  6047.9 1874.33  6060.1 1877.17
  6128.3 1874.32  6225.6 1880.86  6370.3  1881.6  6382.3 1881.63  6402.7 1881.61
#Mann= 14 ,-1 , 0
  3792.1     .07       0  3932.8    .035       0  4214.1     .07       0
  4348.3    .035       0  4741.4     .07       0  4855.5    .035       0
  5009.6    .035       0  5020.8    .035       0  5092.7     .07       0
  5301.8    .035       0  5912.5     .07       0  5973.4    .035       0
  6370.3     .07       0  6382.3    .035       0
Bank Sta=5009.6,5020.8
XS Rating Curve= 0 ,0
Exp/Cntr=0.3,0.1

Type RM Length L Ch R = 1 ,20802   ,517,517,517
BEGIN DESCRIPTION:
Elm 01 30 20801.77
END DESCRIPTION:
XS GIS Cut Line= 3
       1543647.9      6815905.51      1544659.19      6816126.86
      1545730.62      6816335.07
#Sta/Elev= 30
  3966.9 1867.17  4058.6 1866.26  4360.7 1863.03  4515.9 1861.02  4606.8 1860.44
  4629.3 1863.36  4660.9 1857.14  4690.7 1855.49  4731.7 1862.23  4772.6 1854.85
  4797.6 1855.31  4841.5 1863.36  4864.8  1859.8  4967.1 1858.92  4983.3 1855.53
    5039 1858.99    5059 1854.61  5079.4 1858.37  5130.3 1858.64  5145.1 1854.26
  5145.6 1853.76  5156.3 1854.26  5188.9 1859.11    5344  1858.6    5385 1855.08
  5405.8 1858.54  5415.5 1855.92  5715.9 1860.93  5884.1 1872.83  6093.6 1878.45
#Mann= 6 ,-1 , 0
  3966.9    .035       0  4058.6     .07       0  4360.7    .035       0
  4515.9     .07       0  5145.1     .07       0  5156.3     .07       0
Bank Sta=5145.1,5156.3
XS Rating Curve= 0 ,0
Exp/Cntr=0.3,0.1

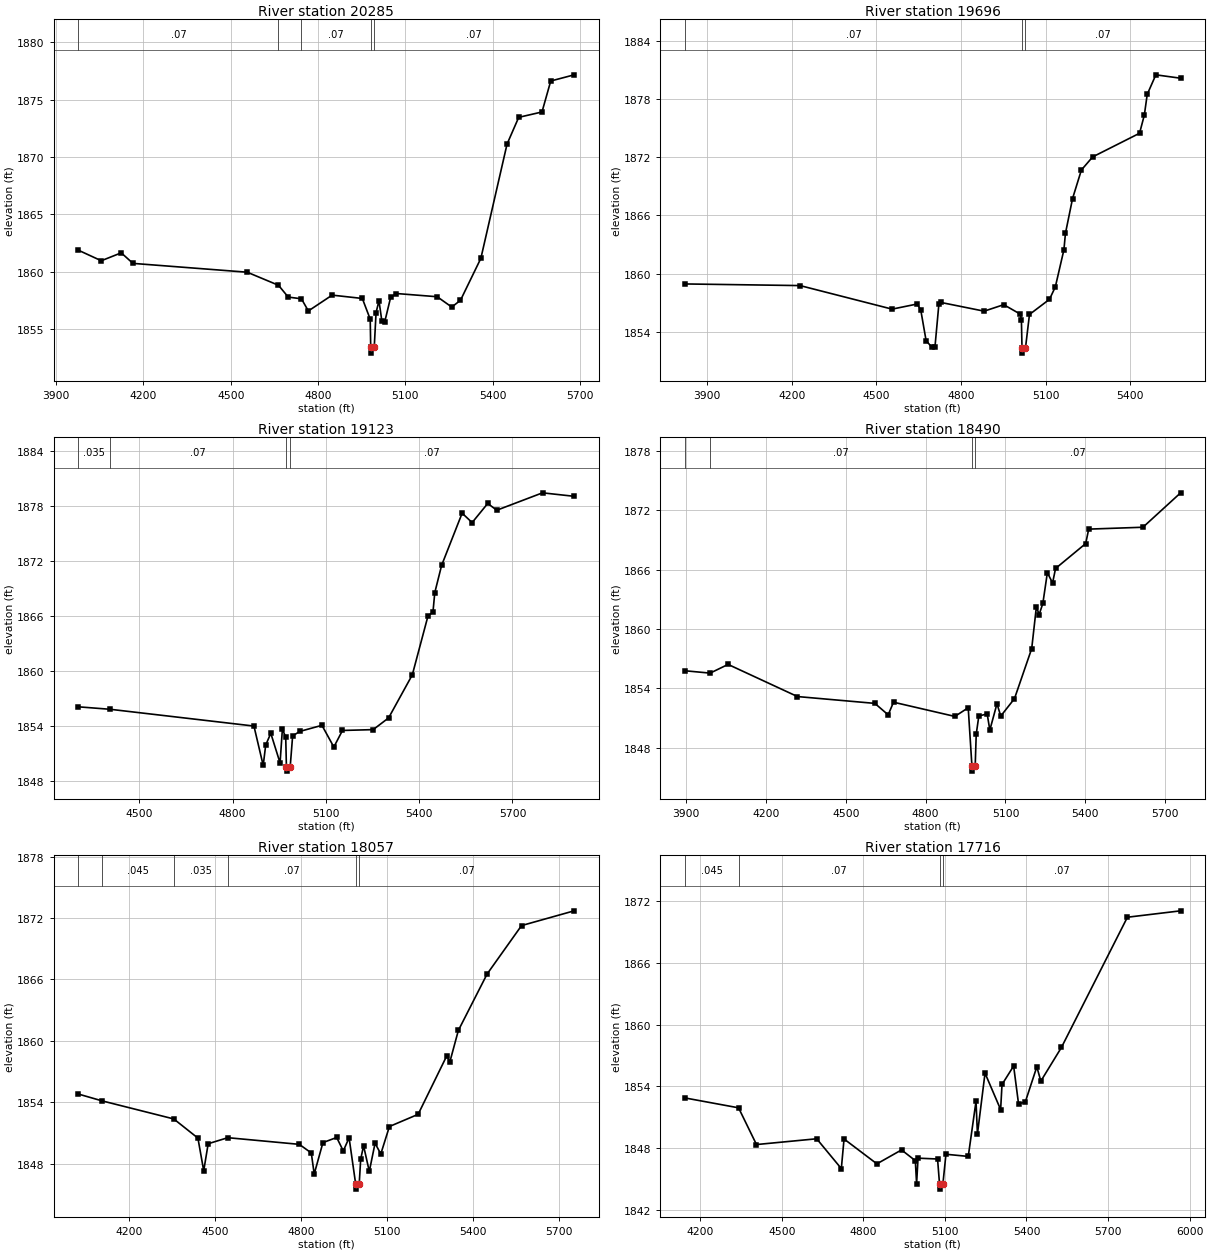
Type RM Length L Ch R = 1 ,20285   ,589,589,589
BEGIN DESCRIPTION:
Elm 01 30 20285.13
END DESCRIPTION:
XS GIS Cut Line= 3
      1544038.53      6816491.44      1545045.47       6816378.6
      1545735.53       6816378.6
#Sta/Elev= 30
  3976.6 1861.86  4055.5 1860.94    4124 1861.63  4164.2 1860.71  4556.7 1859.94
  4664.2  1858.8  4697.6 1857.77    4743 1857.62  4766.8 1856.56  4848.5 1857.94
  4952.2 1857.65  4979.3 1855.84    4981 1853.38  4981.5 1852.88  4993.1 1853.38
  4999.4 1856.42  5009.4 1857.45  5019.4 1855.66  5029.4 1855.63  5049.4 1857.74
  5069.4 1858.08  5209.4  1857.8  5259.4  1856.9  5289.4 1857.49  5359.4 1861.15
  5449.4 1871.12  5489.4 1873.45  5569.4 1873.92  5599.4 1876.62  5679.9 1877.16
#Mann= 5 ,-1 , 0
  3976.6     .07       0  4664.2    .035       0    4743     .07       0
    4981     .07       0  4993.1     .07       0
Bank Sta=4981,4993.1
XS Rating Curve= 0 ,0
Exp/Cntr=0.3,0.1

Type RM Length L Ch R = 1 ,19696   ,573,573,573
BEGIN DESCRIPTION:
Elm 01 30 19695.8
END DESCRIPTION:
XS GIS Cut Line= 3
      1544259.87      6816977.56      1545397.03      6816612.97
      1545951.28      6816504.72
#Sta/Elev= 30
  3820.1 1858.93  4228.9 1858.76  4555.5 1856.33  4644.6 1856.86  4657.1 1856.25
  4676.1 1853.08  4697.1 1852.38  4707.6 1852.45  4721.4 1856.84  4728.6 1857.02
    4882 1856.12  4951.5 1856.79  5010.5 1855.81  5014.2 1855.22  5016.3 1852.29
  5016.8 1851.79  5028.5 1852.29  5042.8 1855.78  5113.7 1857.34  5134.5 1858.62
    5165 1862.46  5170.4 1864.15  5195.6 1867.74    5227 1870.69  5266.9 1872.04
  5433.3 1874.48  5450.3 1876.36  5460.5 1878.49  5491.1 1880.51    5579 1880.16
#Mann= 3 ,-1 , 0
  3820.1     .07       0  5016.3     .07       0  5028.5     .07       0
Bank Sta=5016.3,5028.5
XS Rating Curve= 0 ,0
Exp/Cntr=0.3,0.1

Type RM Length L Ch R = 1 ,19123   ,633,633,633
BEGIN DESCRIPTION:
Elm 01 30 19122.86
END DESCRIPTION:
XS GIS Cut Line= 3
      1544624.49      6817359.49       1545253.8       6817112.1
      1546064.86      6816682.72
#Sta/Elev= 30
  4304.4  1856.1  4406.8 1855.83  4868.9    1854  4898.7  1849.7  4906.7 1851.92
  4923.1 1853.21  4952.9 1849.97  4960.4 1853.68  4971.1 1852.77  4973.3 1849.58
  4973.8 1849.08  4985.5 1849.58  4993.3 1852.92  5015.8 1853.41  5087.5 1854.08
  5125.8 1851.71  5153.5 1853.52  5252.2 1853.61  5301.8 1854.89    5378 1859.59
  5428.2 1865.99  5444.5 1866.47  5450.2 1868.56  5472.2 1871.54  5538.2 1877.24
  5570.3 1876.21  5620.5  1878.3  5649.5 1877.56  5796.6 1879.46  5898.3 1879.08
#Mann= 4 ,-1 , 0
  4304.4    .035       0  4406.8     .07       0  4973.3     .07       0
  4985.5     .07       0
Bank Sta=4973.3,4985.5
XS Rating Curve= 0 ,0
Exp/Cntr=0.3,0.1

Type RM Length L Ch R = 1 ,18490   ,433,433,433
BEGIN DESCRIPTION:
Elm 01 30 18489.63
END DESCRIPTION:
XS GIS Cut Line= 3
      1544602.72      6817441.97      1545709.53      6817368.18
      1546441.53       6817190.6
#Sta/Elev= 30
  3895.4 1855.77  3990.5 1855.53    4058 1856.41  4318.6 1853.16  4609.3 1852.47
  4659.4 1851.31  4679.4 1852.59  4909.9 1851.15    4960 1852.03    4974 1846.12
  4974.5 1845.62  4986.2 1846.12  4990.1 1849.35  4999.9  1851.2  5031.3  1851.4
  5041.2 1849.77    5068 1852.43  5082.3 1851.19  5133.8 1852.95  5198.5 1858.01
  5216.1 1862.24  5226.4 1861.45  5240.3 1862.57  5257.3 1865.68  5276.9 1864.65
  5288.1 1866.11  5401.3 1868.63  5412.6 1870.09  5616.4 1870.28  5757.9 1873.76
#Mann= 4 ,-1 , 0
  3895.4    .035       0  3990.5     .07       0    4974     .07       0
  4986.2     .07       0
Bank Sta=4974,4986.2
XS Rating Curve= 0 ,0
Exp/Cntr=0.3,0.1

Type RM Length L Ch R = 1 ,18057   ,341,341,341
BEGIN DESCRIPTION:
Elm 01 30 18057.22
END DESCRIPTION:
XS GIS Cut Line= 3
      1544793.69      6817602.55      1545757.28      6817754.47
      1546508.18      6817741.44
#Sta/Elev= 30
  4024.8 1854.82  4106.5 1854.16  4357.1 1852.39  4441.2 1850.52  4461.4 1847.33
  4476.9 1849.97  4545.3 1850.56  4794.3 1849.91    4836 1849.07  4846.1 1847.01
  4876.5 1850.08  4924.4 1850.58  4947.4 1849.27  4967.6 1850.55  4990.5 1846.04
    4991 1845.54  5002.8 1846.04    5008 1848.46    5018 1849.77    5038 1847.27
    5058 1850.02    5078 1848.97    5108 1851.65    5208 1852.84  5308.1 1858.57
  5318.1 1857.92  5348.1 1861.03  5448.1 1866.53  5568.1 1871.26  5751.3  1872.7
#Mann= 6 ,-1 , 0
  4024.8     .07       0  4106.5    .045       0  4357.1    .035       0
  4545.3     .07       0  4990.5     .07       0  5002.8     .07       0
Bank Sta=4990.5,5002.8
XS Rating Curve= 0 ,0
Exp/Cntr=0.3,0.1

Type RM Length L Ch R = 1 ,17716   ,644,644,644
BEGIN DESCRIPTION:
Elm 01 30 17716.44
END DESCRIPTION:
XS GIS Cut Line= 3
      1544863.13      6817945.43      1545700.85      6818040.92
      1546655.69      6818262.27
#Sta/Elev= 30
  4143.5 1852.89  4341.2 1851.93  4407.1 1848.37  4628.5 1848.93  4719.1 1846.04
  4729.1 1848.91  4849.9  1846.5  4940.5 1847.85  4991.2 1846.81  4995.9 1844.57
  5001.2 1847.05    5073 1846.97  5080.2 1844.55  5080.7 1844.05  5092.6 1844.55
  5103.8 1847.43  5185.9 1847.22  5214.4 1852.57  5219.6 1849.38  5247.5 1855.29
  5304.9 1851.76    5310 1854.19  5352.7 1855.98  5370.7 1852.33  5395.4 1852.48
    5438  1855.9  5452.8 1854.52  5528.5 1857.78  5771.1  1870.4  5966.8 1871.02
#Mann= 4 ,-1 , 0
  4143.5    .045       0  4341.2     .07       0  5080.2     .07       0
  5092.6     .07       0
Bank Sta=5080.2,5092.6
XS Rating Curve= 0 ,0
Exp/Cntr=0.3,0.1

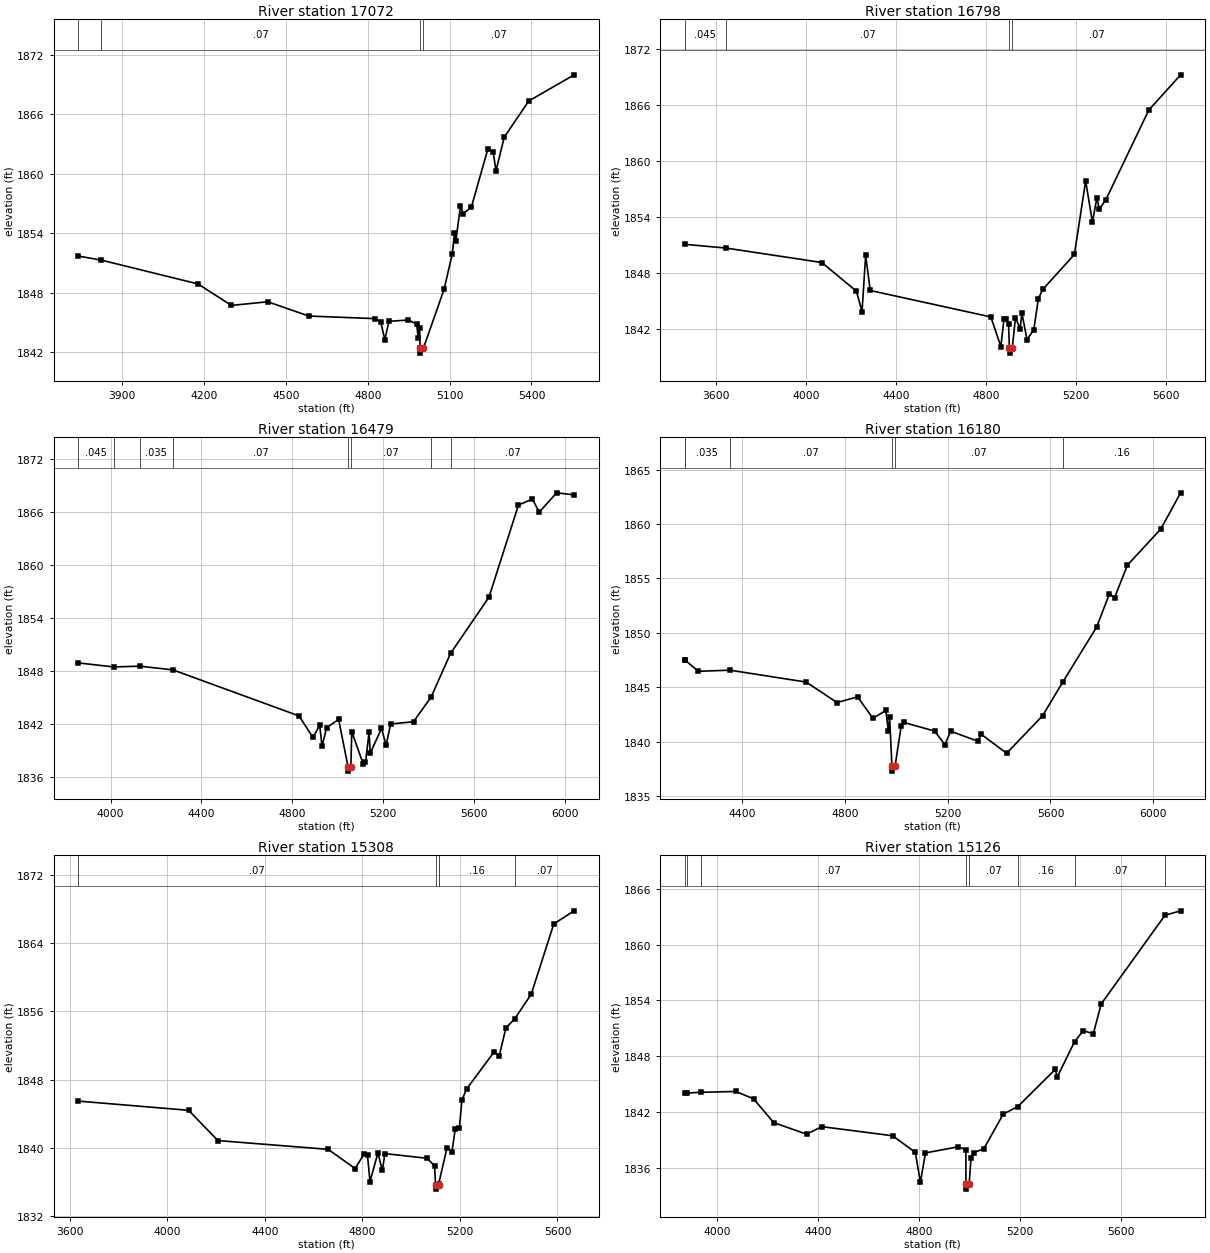
Type RM Length L Ch R = 1 ,17072   ,274,274,274
BEGIN DESCRIPTION:
Elm 01 30 17071.66
END DESCRIPTION:
XS GIS Cut Line= 3
      1544910.91      6818201.51      1546156.58      6818405.51
      1546711.03      6818440.16
#Sta/Elev= 30
  3738.7 1851.68  3823.3 1851.27  4177.3 1848.87    4300  1846.7  4432.8 1847.07
  4583.9 1845.63  4827.1 1845.37  4847.4 1845.06  4862.1 1843.25  4877.8  1845.1
  4948.7 1845.23  4979.1 1844.82  4984.8 1843.42  4989.9 1844.46  4991.4 1842.39
  4991.9 1841.89  5003.8 1842.39  5079.5 1848.31  5109.6 1851.89  5117.8 1853.97
  5122.9 1853.24  5139.7 1856.73  5149.7 1855.95  5179.7 1856.62  5239.8 1862.45
  5259.9 1862.13  5269.9 1860.27    5300 1863.66  5390.1 1867.32  5556.5 1869.96
#Mann= 4 ,-1 , 0
  3738.7    .045       0  3823.3     .07       0  4991.4     .07       0
  5003.8     .07       0
Bank Sta=4991.4,5003.8
XS Rating Curve= 0 ,0
Exp/Cntr=0.3,0.1

Type RM Length L Ch R = 1 ,16798   ,319,319,319
BEGIN DESCRIPTION:
Elm 01 30 16798.15
END DESCRIPTION:
XS GIS Cut Line= 3
      1544650.48      6818357.76      1546143.56      6818678.94
       1546816.3      6818665.92
#Sta/Elev= 30
  3463.3 1851.04  3645.9 1850.64  4071.4 1849.09  4224.8 1846.01  4249.7 1843.83
  4265.8 1849.86  4286.2 1846.09  4821.4 1843.25  4865.7 1840.07  4879.5 1842.98
  4889.7 1842.98  4899.9 1842.53  4903.7 1839.87  4904.2 1839.37  4916.1 1839.87
  4930.6 1843.19  4951.1 1841.97  4959.2 1843.66  4981.8 1840.82    5012 1841.89
    5032  1845.2    5052 1846.21    5192 1849.95    5242 1857.84    5272 1853.42
    5292 1856.05  5302.4 1854.81    5332 1855.84  5522.1 1865.44  5663.4 1869.22
#Mann= 4 ,-1 , 0
  3463.3    .045       0  3645.9     .07       0  4903.7     .07       0
  4916.1     .07       0
Bank Sta=4903.7,4916.1
XS Rating Curve= 0 ,0
Exp/Cntr=0.3,0.1

Type RM Length L Ch R = 1 ,16479   ,299,299,299
BEGIN DESCRIPTION:
Elm 01 30 16479.02
END DESCRIPTION:
XS GIS Cut Line= 3
      1544871.91      6818765.76      1546004.67      6818926.34
      1547037.64      6819052.21
#Sta/Elev= 30
  3857.5 1848.91  4012.7 1848.45  4127.9 1848.54  4274.2 1848.12  4830.2 1842.91
  4890.8 1840.49  4921.1 1841.84  4931.2 1839.48  4951.4 1841.57  5004.3 1842.52
  5045.8 1837.17  5046.3 1836.67  5058.2 1837.17  5062.4 1841.12  5112.7 1837.48
  5122.8 1837.68  5138.6 1841.06  5143.7 1838.69  5193.3  1841.5  5213.5  1839.6
  5233.6    1842  5334.4 1842.26  5411.6 1845.03    5498    1850  5666.8 1856.34
  5796.7 1866.75  5858.2 1867.44  5888.4 1865.96    5965 1868.14  6042.2 1867.91
#Mann= 8 ,-1 , 0
  3857.5    .045       0  4012.7     .07       0  4127.9    .035       0
  4274.2     .07       0  5045.8     .07       0  5058.2     .07       0
  5411.6     .16       0    5498     .07       0
Bank Sta=5045.8,5058.2
XS Rating Curve= 0 ,0
Exp/Cntr=0.3,0.1

Type RM Length L Ch R = 1 ,16180   ,872,872,872
BEGIN DESCRIPTION:
Elm 01 30 16179.85
END DESCRIPTION:
XS GIS Cut Line= 3
       1545032.4      6819147.69      1545852.76      6819173.74
      1546961.96      6819117.41
#Sta/Elev= 30
  4175.6 1847.51  4175.8 1847.51  4228.2 1846.47  4351.7 1846.57  4648.4 1845.48
  4768.5  1843.6  4848.5 1844.12  4908.6 1842.15  4958.6 1842.87  4968.4 1841.03
  4973.4 1842.25  4982.4  1837.8  4982.9  1837.3  4994.9  1837.8  5018.6 1841.45
  5028.7 1841.77  5148.8 1840.98  5188.9 1839.72    5211 1840.97    5319 1840.03
    5329 1840.71  5429.2 1838.94  5569.3 1842.39  5647.2 1845.45  5779.6 1850.52
  5829.7 1853.59  5849.7 1853.23  5899.8 1856.22  6029.9 1859.54    6107 1862.86
#Mann= 6 ,-1 , 0
  4175.6    .045       0  4175.8    .035       0  4351.7     .07       0
  4982.4     .07       0  4994.9     .07       0  5647.2     .16       0
Bank Sta=4982.4,4994.9
XS Rating Curve= 0 ,0
Exp/Cntr=0.3,0.1

Type RM Length L Ch R = 1 ,15308   ,182,182,182
BEGIN DESCRIPTION:
Elm 01 30 15307.62
END DESCRIPTION:
XS GIS Cut Line= 3
      1545193.05      6819421.13      1546213.01      6819451.51
      1547206.92      6819260.54
#Sta/Elev= 30
    3636 1845.47  4088.1 1844.39  4208.2 1840.84    4660 1839.81  4770.4 1837.56
  4806.8 1839.23  4821.4 1839.09  4831.5 1836.03  4863.9 1839.37  4882.5 1837.34
  4892.6 1839.31  5065.8 1838.76  5096.3 1837.87  5100.2 1835.64  5100.7 1835.14
  5112.8 1835.64  5113.1 1835.76  5147.2 1839.98  5167.6 1839.54  5180.7 1842.14
  5198.1 1842.33  5208.3 1845.57  5227.5 1846.89  5341.6 1851.29  5361.1 1850.74
  5388.5 1854.04  5425.6 1855.16  5492.4 1858.01  5585.1 1866.27  5668.5  1867.8
#Mann= 5 ,-1 , 0
    3636     .07       0  5100.2     .07       0  5112.8     .07       0
  5113.1     .16       0  5425.6     .07       0
Bank Sta=5100.2,5112.8
XS Rating Curve= 0 ,0
Exp/Cntr=0.3,0.1

Type RM Length L Ch R = 1 ,15126   ,371,371,371
BEGIN DESCRIPTION:
Elm 01 30 15125.67
END DESCRIPTION:
XS GIS Cut Line= 3
       1545423.1      6819533.98      1546542.87      6819542.66
      1547376.16      6819425.48
#Sta/Elev= 30
  3873.3 1844.03  3880.8 1844.03  3935.5 1844.11  4075.2  1844.2  4145.2 1843.41
  4225.2 1840.84  4355.2  1839.6  4415.2 1840.41  4695.2 1839.43  4785.2 1837.64
  4805.2 1834.41  4825.2 1837.58  4955.2 1838.24  4985.2 1837.92  4985.4 1834.18
  4985.9 1833.68    4998 1834.18  5005.4 1836.99  5015.5 1837.61  5055.9 1838.02
  5132.9 1841.76  5190.3 1842.57  5338.6 1846.57  5346.7 1845.77    5415 1849.56
  5449.7 1850.76  5489.2 1850.41  5520.4 1853.63  5772.8 1863.18  5834.6 1863.66
#Mann= 8 ,-1 , 0
  3873.3     .07       0  3880.8    .035       0  3935.5     .07       0
  4985.4     .07       0    4998     .07       0  5190.3     .16       0
    5415     .07       0  5772.8     .16       0
Bank Sta=4985.4,4998
XS Rating Curve= 0 ,0
Exp/Cntr=0.3,0.1

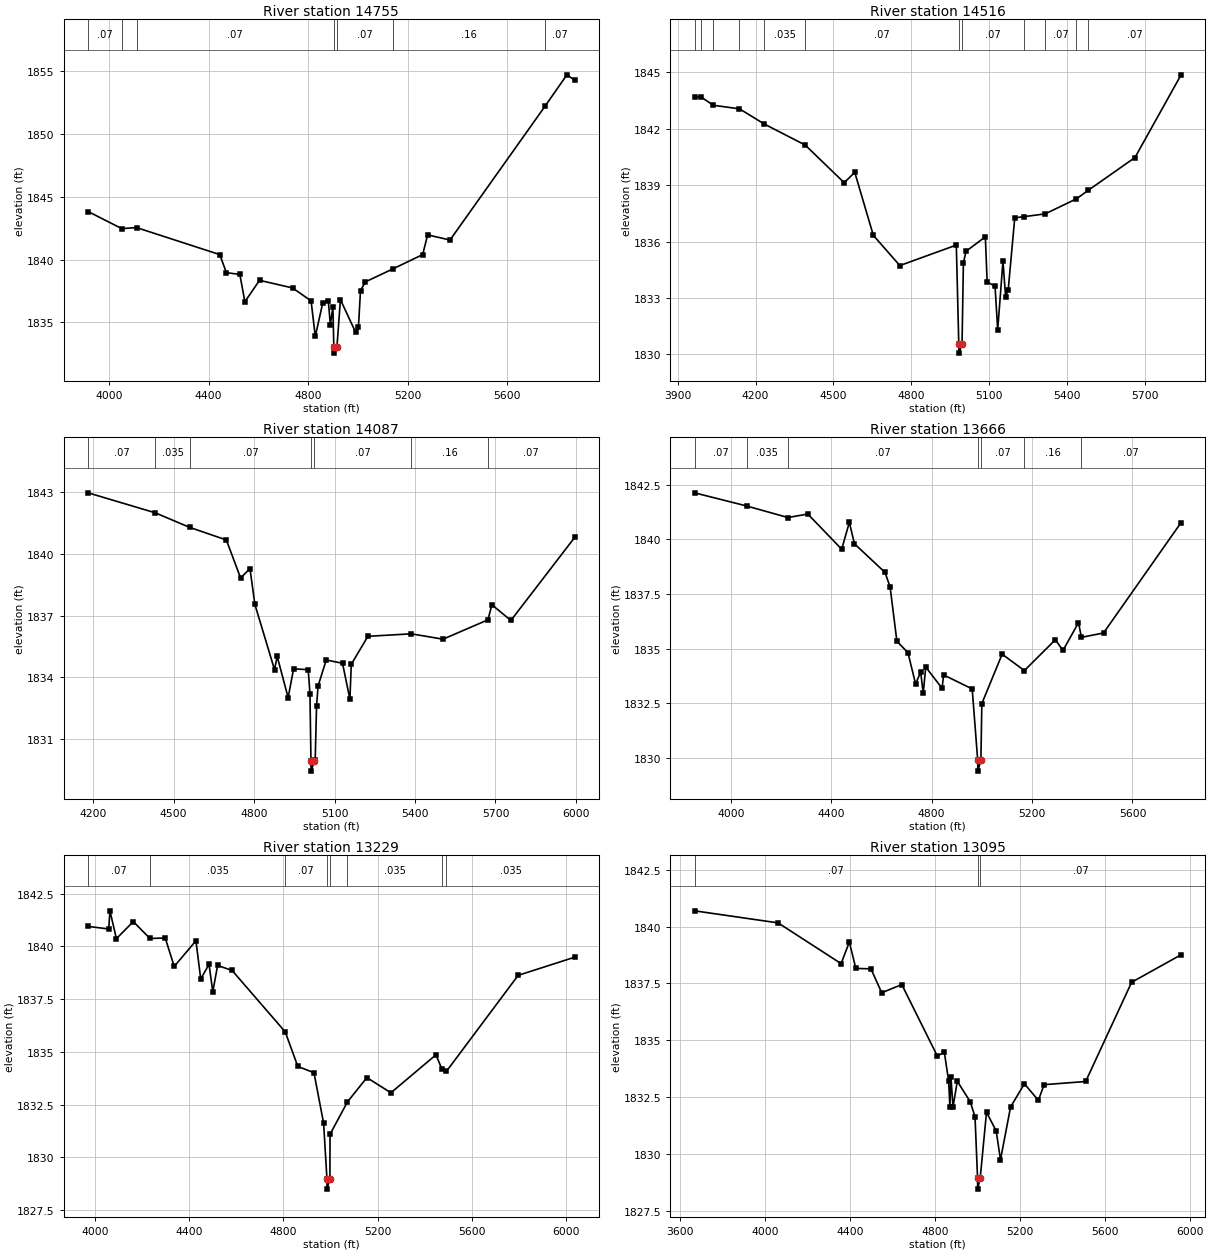
Type RM Length L Ch R = 1 ,14755   ,239,239,239
BEGIN DESCRIPTION:
Elm 01 30 14754.77
END DESCRIPTION:
XS GIS Cut Line= 3
      1545531.55       6819590.4      1546603.63      6819750.99
      1547476.07      6819755.33
#Sta/Elev= 30
  3915.3 1843.83  4050.5 1842.47  4110.3 1842.55  4444.6  1840.4  4471.4 1838.96
  4525.5 1838.82  4545.7 1836.64  4604.6 1838.35  4737.8 1837.74    4812 1836.71
  4828.8 1833.88  4859.2 1836.58  4881.2 1836.73  4889.5  1834.8  4899.6 1836.23
  4903.4 1833.05  4903.9 1832.55    4916 1833.05    4930 1836.81  4990.6 1834.23
  5002.5 1834.65  5010.7 1837.53  5030.7 1838.23  5141.1 1839.26  5260.7  1840.4
  5280.7 1841.97  5370.7 1841.56  5752.1  1852.2  5840.7 1854.72  5871.8  1854.3
#Mann= 7 ,-1 , 0
  3915.3     .07       0  4050.5    .035       0  4110.3     .07       0
  4903.4     .07       0    4916     .07       0  5141.1     .16       0
  5752.1     .07       0
Bank Sta=4903.4,4916
XS Rating Curve= 0 ,0
Exp/Cntr=0.3,0.1

Type RM Length L Ch R = 1 ,14516   ,429,429,429
BEGIN DESCRIPTION:
Elm 01 30 14515.5
END DESCRIPTION:
XS GIS Cut Line= 3
      1545440.47      6819703.26      1546447.38      6819907.24
      1547280.36      6820054.75
#Sta/Elev= 30
  3965.2 1843.71    3991 1843.68  4037.7 1843.25  4138.1 1843.06  4232.6 1842.26
  4391.4 1841.13  4541.2 1839.13    4582 1839.68  4653.4 1836.33  4755.5 1834.72
    4973 1835.81  4982.5 1830.56    4983 1830.06  4995.1 1830.56  5000.3 1834.87
  5010.5 1835.48  5084.8 1836.25  5091.7 1833.86  5122.2 1833.61  5132.3 1831.29
  5152.6 1834.95  5162.8 1833.05  5172.9 1833.44    5198 1837.26  5232.7 1837.32
  5315.1 1837.47  5435.4 1838.27  5480.6 1838.72    5661 1840.47  5838.5 1844.87
#Mann= 12 ,-1 , 0
  3965.2    .035       0    3991     .07       0  4037.7    .035       0
  4138.1     .07       0  4232.6    .035       0  4391.4     .07       0
  4982.5     .07       0  4995.1     .07       0  5232.7     .16       0
  5315.1     .07       0  5435.4     .16       0  5480.6     .07       0
Bank Sta=4982.5,4995.1
XS Rating Curve= 0 ,0
Exp/Cntr=0.3,0.1

Type RM Length L Ch R = 1 ,14087   ,421,421,421
BEGIN DESCRIPTION:
Elm 01 30 14086.87
END DESCRIPTION:
XS GIS Cut Line= 3
      1545401.35      6819950.64      1546208.67      6820098.22
      1547189.61      6820254.47
#Sta/Elev= 30
  4181.1 1842.97  4431.2    1842  4560.1 1841.29  4696.5 1840.68  4749.7 1838.83
  4784.6 1839.29  4802.9 1837.55  4876.1 1834.38  4886.2 1835.02  4926.9 1833.02
  4947.2 1834.42  5001.8 1834.38  5008.2 1833.22    5012 1829.95  5012.5 1829.45
  5024.7 1829.95  5027.8 1829.99  5032.9 1832.62  5038.6 1833.59    5069 1834.85
  5129.7 1834.69  5157.2 1832.94  5162.3 1834.64  5224.4    1836  5386.2 1836.12
  5504.4 1835.86  5671.8  1836.8  5686.7 1837.53  5757.5 1836.77  5995.1  1840.8
#Mann= 7 ,-1 , 0
  4181.1     .07       0  4431.2    .035       0  4560.1     .07       0
    5012     .07       0  5024.7     .07       0  5386.2     .16       0
  5671.8     .07       0
Bank Sta=5012,5024.7
XS Rating Curve= 0 ,0
Exp/Cntr=0.3,0.1

Type RM Length L Ch R = 1 ,13666   ,437,437,437
BEGIN DESCRIPTION:
Elm 01 30 13665.81
END DESCRIPTION:
XS GIS Cut Line= 3
      1545327.56      6820176.33      1546464.74      6820371.65
      1547240.87      6820480.05
#Sta/Elev= 30
  3856.2 1842.13    4063 1841.53    4228    1841  4307.1 1841.16  4442.1 1839.55
  4472.5 1840.78  4492.8  1839.8  4614.6 1838.49  4634.9 1837.82  4661.9 1835.34
  4705.9 1834.82  4736.3 1833.39  4756.6 1833.93  4766.8 1832.96  4776.8 1834.16
  4841.8 1833.19    4848  1833.8  4961.8 1833.16  4983.7  1829.9  4984.2  1829.4
  4996.4  1829.9  5000.2 1832.49    5081 1834.75  5169.6    1834    5293 1835.41
  5323.3 1834.92  5385.1 1836.19  5396.9 1835.52  5484.9 1835.72  5793.7 1840.77
#Mann= 7 ,-1 , 0
  3856.2     .07       0    4063    .035       0    4228     .07       0
  4983.7     .07       0  4996.4     .07       0  5169.6     .16       0
  5396.9     .07       0
Bank Sta=4983.7,4996.4
XS Rating Curve= 0 ,0
Exp/Cntr=0.3,0.1

Type RM Length L Ch R = 1 ,13229   ,134,134,134
BEGIN DESCRIPTION:
Elm 01 30 13333
END DESCRIPTION:
XS GIS Cut Line= 3
      1545297.55      6820483.65       1546352.2      6820713.68
      1547320.05      6820908.99
#Sta/Elev= 30
  3970.2 1840.95  4057.8 1840.83  4062.9 1841.69  4090.4 1840.37  4162.1 1841.18
  4232.8 1840.38  4297.9  1840.4    4336 1839.05  4428.2 1840.27  4448.6 1838.46
  4483.9 1839.15  4499.8 1837.85  4520.3  1839.1    4582 1838.86  4807.5 1835.95
    4861 1834.31  4929.7 1834.01  4970.6 1831.62  4984.7 1828.99  4985.2 1828.49
  4997.4 1828.99  4997.9 1831.09  5072.1 1832.63  5154.5 1833.78  5256.5 1833.06
  5447.9 1834.86  5473.8 1834.17    5492 1834.07  5797.2 1838.63    6037 1839.49
#Mann= 8 ,-1 , 0
  3970.2     .07       0  4232.8    .035       0  4807.5     .07       0
  4984.7     .07       0  4997.4     .07       0  5072.1    .035       0
  5473.8     .07       0    5492    .035       0
Bank Sta=4984.7,4997.4
XS Rating Curve= 0 ,0
Exp/Cntr=0.3,0.1

Type RM Length L Ch R = 1 ,13095   ,678,678,678
BEGIN DESCRIPTION:
Elm 01 30 12878.01
END DESCRIPTION:
XS GIS Cut Line= 3
       1544998.2      6820603.24      1546466.94      6820863.65
      1547241.08      6821052.14
#Sta/Elev= 30
  3668.6 1840.69  4061.4 1840.16  4357.8 1838.37  4396.6 1839.32    4427 1838.16
  4498.1 1838.14  4548.9 1837.09  4643.2 1837.45  4810.4 1834.31  4843.4 1834.48
  4863.7  1833.2  4869.5 1832.09  4874.5 1833.38  4884.1 1832.07  4904.4  1833.2
  4965.3  1832.3  4987.7 1831.64  4999.6 1828.96  5000.1 1828.46  5012.3 1828.96
  5041.7 1831.84  5087.2 1831.02  5107.5 1829.75  5154.9 1832.07    5220 1833.09
  5285.6 1832.36  5312.6 1833.05  5508.2 1833.19  5724.3 1837.55    5957 1838.76
#Mann= 3 ,-1 , 0
  3668.6     .07       0  4999.6     .07       0  5012.3     .07       0
Bank Sta=4999.6,5012.3
XS Rating Curve= 0 ,0
Exp/Cntr=0.3,0.1