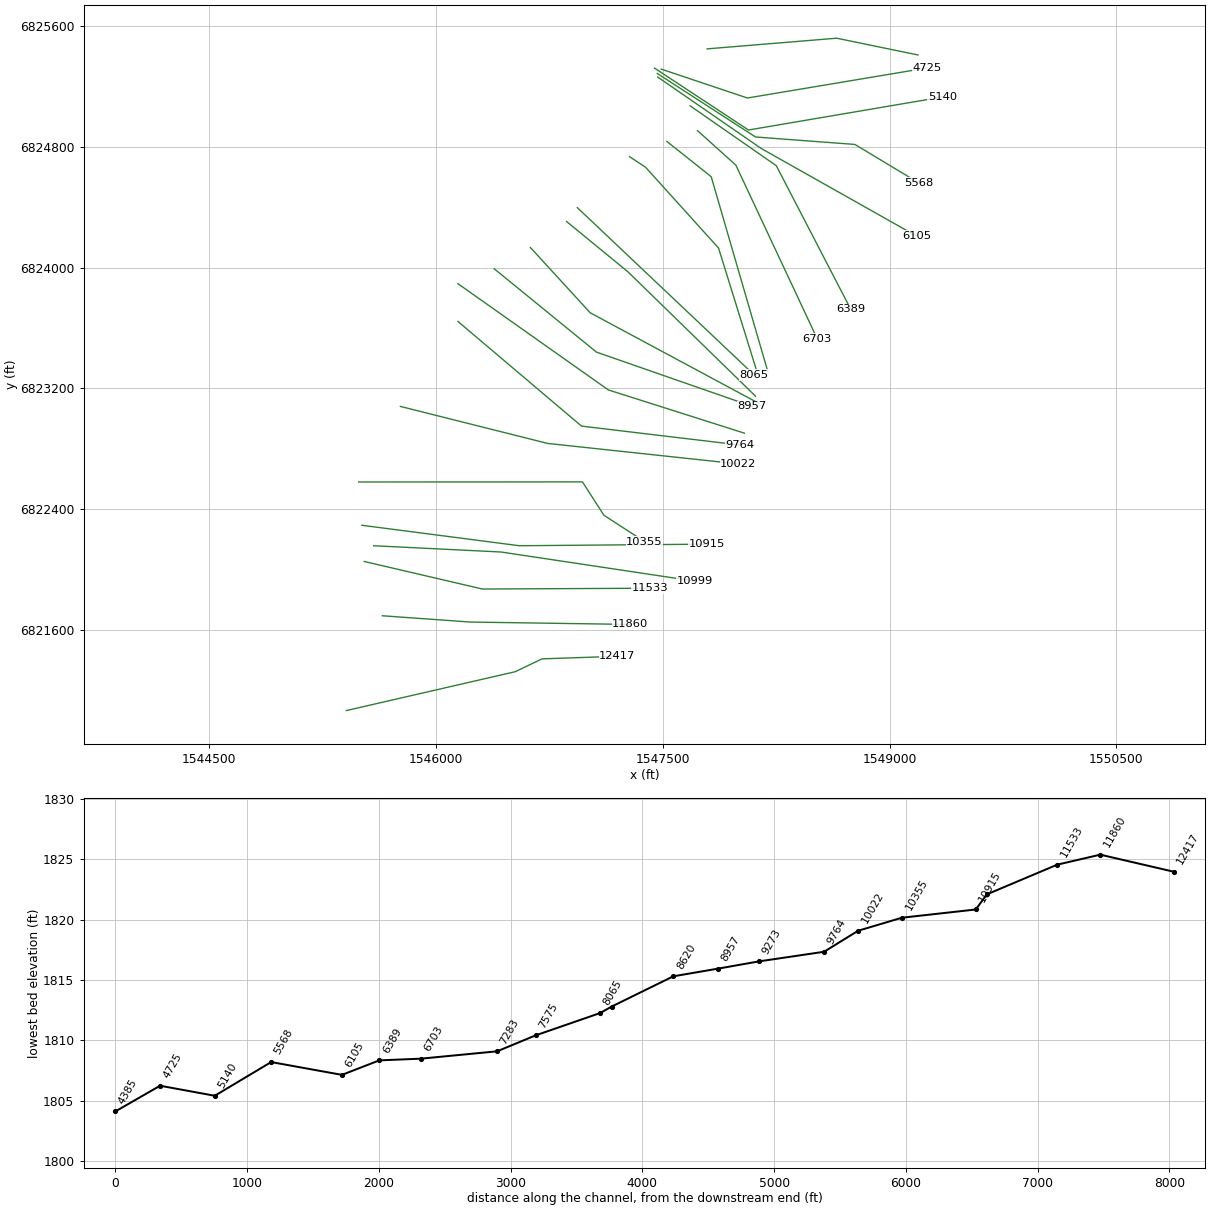
HEC-RAS study Elm 01 30.prj: Elm 01 30 Base Level Engineering

--- Elm 01 30.g01 (geometry) --- (continued)

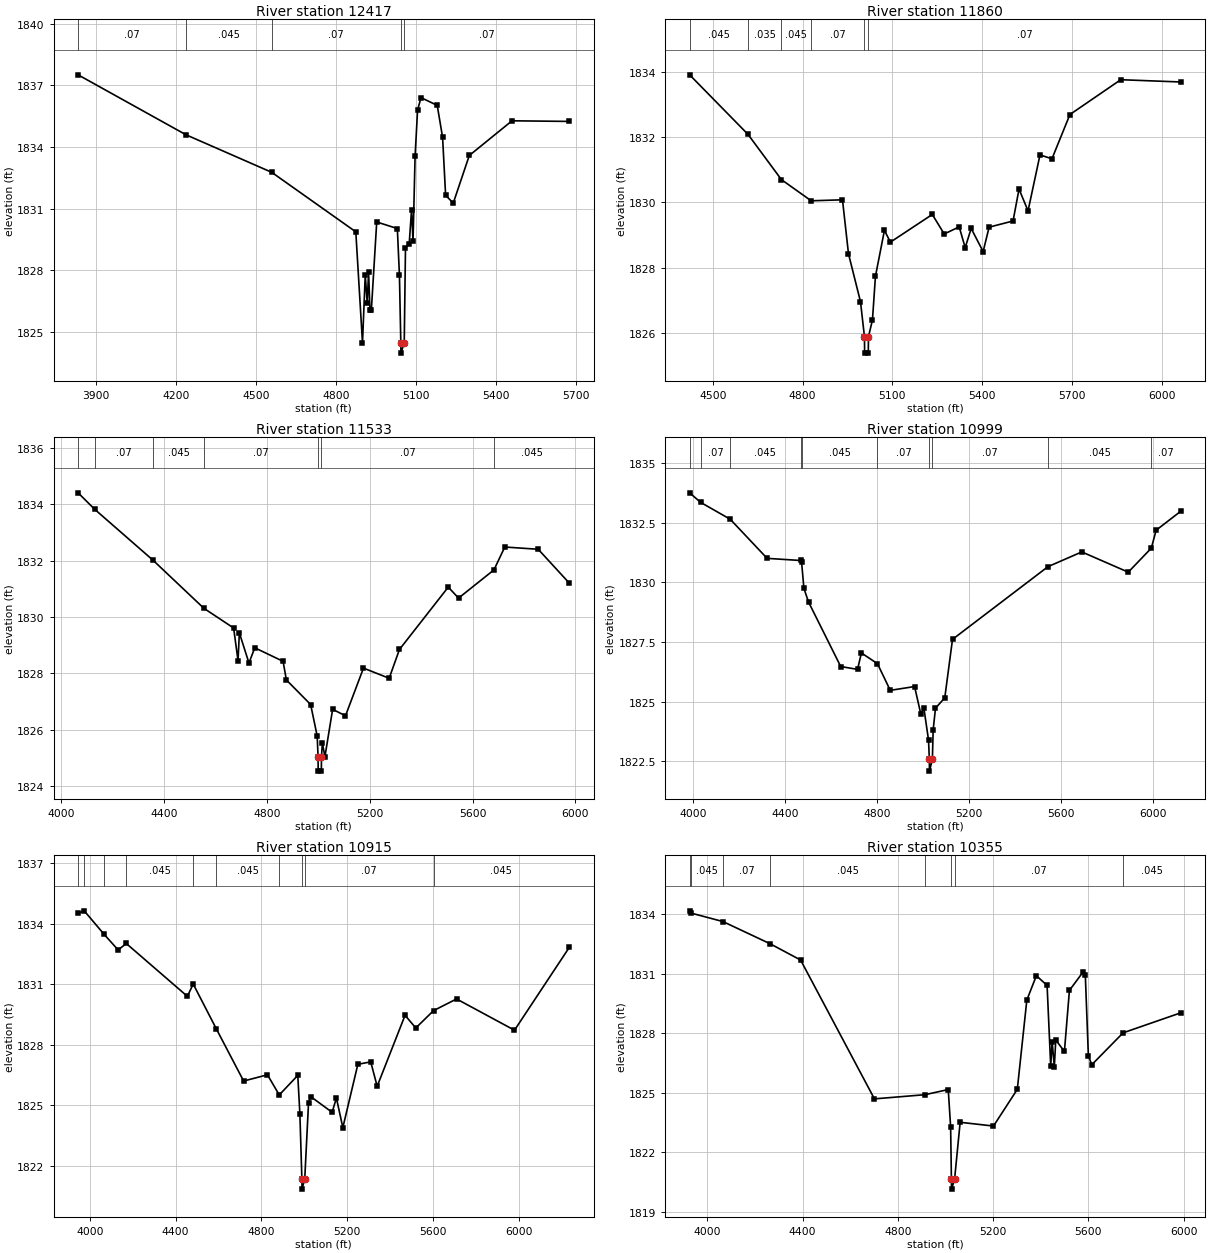
Type RM Length L Ch R = 1 ,12417   ,557,557,557
BEGIN DESCRIPTION:
Elm 01 30 12248.24
END DESCRIPTION:
XS GIS Cut Line= 4
      1545407.65      6821068.12       1546524.3      6821325.25
      1546701.86      6821410.21      1547199.75      6821427.38
#Sta/Elev= 30
  3834.2 1837.52  4238.4  1834.6  4559.8 1832.77  4874.9 1829.87    4900 1824.46
  4910.3 1827.77  4917.7  1826.4  4922.8 1827.91  4927.9 1826.06  4933.2 1826.06
  4953.3 1830.35  5030.6 1830.03  5038.4 1827.76  5043.6 1824.46  5044.1 1823.96
  5056.4 1824.46  5061.1 1829.08    5075 1829.28  5083.8 1830.95  5089.3  1829.4
  5097.1 1833.56  5106.4  1835.8  5119.3 1836.41  5180.1 1836.03  5200.1 1834.48
  5211.5 1831.65  5240.1 1831.27  5300.2 1833.59  5460.3 1835.28  5675.1 1835.25
#Mann= 5 ,-1 , 0
  3834.2     .07       0  4238.4    .045       0  4559.8     .07       0
  5043.6     .07       0  5056.4     .07       0
Bank Sta=5043.6,5056.4
XS Rating Curve= 0 ,0
Exp/Cntr=0.3,0.1

Type RM Length L Ch R = 1 ,11860   ,327,327,327
BEGIN DESCRIPTION:
Elm 01 30 11860.4
END DESCRIPTION:
XS GIS Cut Line= 3
      1545645.29      6821695.44      1546228.63      6821653.77
      1547285.89      6821638.15
#Sta/Elev= 30
  4422.4 1833.92  4617.6 1832.09  4729.3  1830.7  4828.8 1830.05  4933.4 1830.08
  4953.5 1828.42  4993.6 1826.95  5006.9 1825.87  5007.4 1825.37  5019.7 1825.37
  5020.2 1825.87  5033.6 1826.39  5043.6 1827.73  5073.6 1829.14  5093.6 1828.78
  5233.6 1829.63  5273.6 1829.03  5323.6 1829.25  5343.6 1828.61  5363.6  1829.2
  5403.6 1828.49  5423.6 1829.24  5503.6 1829.43  5523.6 1830.41  5553.7 1829.74
  5593.7 1831.46  5633.7 1831.34  5693.7  1832.7  5863.7 1833.77  6064.6  1833.7
#Mann= 6 ,-1 , 0
  4422.4    .045       0  4617.6    .035       0  4729.3    .045       0
  4828.8     .07       0  5006.9     .07       0  5020.2     .07       0
Bank Sta=5006.9,5020.2
XS Rating Curve= 0 ,0
Exp/Cntr=0.3,0.1

Type RM Length L Ch R = 1 ,11533   ,534,534,534
BEGIN DESCRIPTION:
Elm 01 30 11532.65
END DESCRIPTION:
XS GIS Cut Line= 3
      1545525.52      6822054.81      1546306.76      6821872.52
      1547416.12      6821877.73
#Sta/Elev= 30
  4064.7  1834.4  4128.8 1833.82  4356.5 1832.01    4554 1830.31    4670 1829.61
  4687.1 1828.45  4692.2 1829.44  4729.6 1828.37  4752.2 1828.91  4862.4 1828.43
  4875.2 1827.77  4969.6  1826.9  4995.2 1825.78  4998.5 1825.04    4999 1824.54
  5011.3 1824.54  5011.8 1825.04  5015.2 1825.54  5025.2 1825.05  5055.2 1826.73
  5105.2  1826.5  5175.2 1828.19  5275.2 1827.83  5315.2 1828.85  5505.2 1831.06
  5545.2 1830.67    5683 1831.67  5725.2 1832.48  5855.2  1832.4  5976.3  1831.2
#Mann= 7 ,-1 , 0
  4064.7    .035       0  4128.8     .07       0  4356.5    .045       0
    4554     .07       0  4998.5     .07       0  5011.8     .07       0
    5683    .045       0
Bank Sta=4998.5,5011.8
XS Rating Curve= 0 ,0
Exp/Cntr=0.3,0.1

Type RM Length L Ch R = 1 ,10999   ,84,84,84
BEGIN DESCRIPTION:
Elm 01 30 10999.11
END DESCRIPTION:
XS GIS Cut Line= 3
      1545587.99      6822158.98      1546431.76      6822117.31
      1547711.47      6821924.84
#Sta/Elev= 30
  3984.4 1833.76  4032.2 1833.36  4161.3 1832.65  4321.8 1831.01  4467.2 1830.92
  4471.9 1830.85    4482 1829.75    4502 1829.18  4642.2 1826.47  4715.6 1826.35
  4732.3 1827.04  4802.2 1826.59    4858 1825.47  4963.9 1825.63  4990.9 1824.48
  5004.4 1824.72  5024.6 1823.39  5028.1 1822.58  5028.6 1822.08  5041.4 1822.58
  5044.8 1823.81  5054.9 1824.72  5095.4 1825.16    5129 1827.61  5544.5 1830.66
    5692 1831.28  5894.3 1830.43  5994.8 1831.44  6015.6 1832.19  6123.3 1832.99
#Mann= 10 ,-1 , 0
  3984.4    .035       0  4032.2     .07       0  4161.3    .045       0
  4467.2     .07       0  4471.9    .045       0  4802.2     .07       0
  5028.1     .07       0  5041.4     .07       0  5544.5    .045       0
  5994.8     .07       0
Bank Sta=5028.1,5041.4
XS Rating Curve= 0 ,0
Exp/Cntr=0.3,0.1

Type RM Length L Ch R = 1 ,10915   ,560,560,560
BEGIN DESCRIPTION:
Elm 01 30 10915.34
END DESCRIPTION:
XS GIS Cut Line= 3
       1545509.9      6822294.39      1546551.55      6822158.98
      1547790.59      6822169.39
#Sta/Elev= 30
  3945.9  1834.5  3974.4 1834.63  4066.6 1833.47  4132.6 1832.69  4170.5 1833.01
  4455.2 1830.39  4482.4    1831  4589.5 1828.79  4717.4 1826.19  4828.4  1826.5
  4883.4  1825.5  4969.8 1826.47  4979.6 1824.55  4988.9 1821.33  4989.4 1820.83
  5002.2 1821.33  5019.8 1825.09  5029.8 1825.42  5129.8 1824.64  5149.8 1825.35
  5179.8 1823.88  5249.8 1827.02  5309.8 1827.14  5339.8 1825.93  5469.8 1829.45
  5519.8 1828.82  5602.4 1829.68  5709.8 1830.26  5979.8 1828.71  6235.4 1832.82
#Mann= 10 ,-1 , 0
  3945.9     .07       0  3974.4    .035       0  4066.6     .07       0
  4170.5    .045       0  4482.4     .07       0  4589.5    .045       0
  4883.4     .07       0  4988.9     .07       0  5002.2     .07       0
  5602.4    .045       0
Bank Sta=4988.9,5002.2
XS Rating Curve= 0 ,0
Exp/Cntr=0.3,0.1

Type RM Length L Ch R = 1 ,10355   ,333,333,333
BEGIN DESCRIPTION:
Elm 01 30 10317.06
END DESCRIPTION:
XS GIS Cut Line= 4
      1545489.01      6822580.85      1546969.02      6822581.47
      1547111.04      6822360.63       1547379.7      6822186.38
#Sta/Elev= 30
  3925.9 1834.18  3930.5 1834.07  4065.5 1833.64  4263.8 1832.52  4391.9  1831.7
  4701.9  1824.7  4913.8 1824.91  5011.9 1825.17  5021.9 1823.29  5025.2 1820.65
  5025.7 1820.15  5038.5 1820.65  5061.9 1823.52  5201.9 1823.33  5301.9 1825.18
  5341.9 1829.68  5381.9 1830.91    5427 1830.42  5442.2 1826.35  5448.2 1827.57
  5457.4 1826.32  5463.4 1827.67  5499.7 1827.09  5520.8 1830.17  5578.3  1831.1
  5587.5 1830.94  5600.3 1826.88  5614.6 1826.42  5746.2 1828.03  5988.7 1829.04
#Mann= 8 ,-1 , 0
  3925.9     .07       0  3930.5    .045       0  4065.5     .07       0
  4263.8    .045       0  4913.8     .07       0  5025.2     .07       0
  5038.5     .07       0  5746.2    .045       0
Bank Sta=5025.2,5038.5
XS Rating Curve= 0 ,0
Exp/Cntr=0.3,0.1

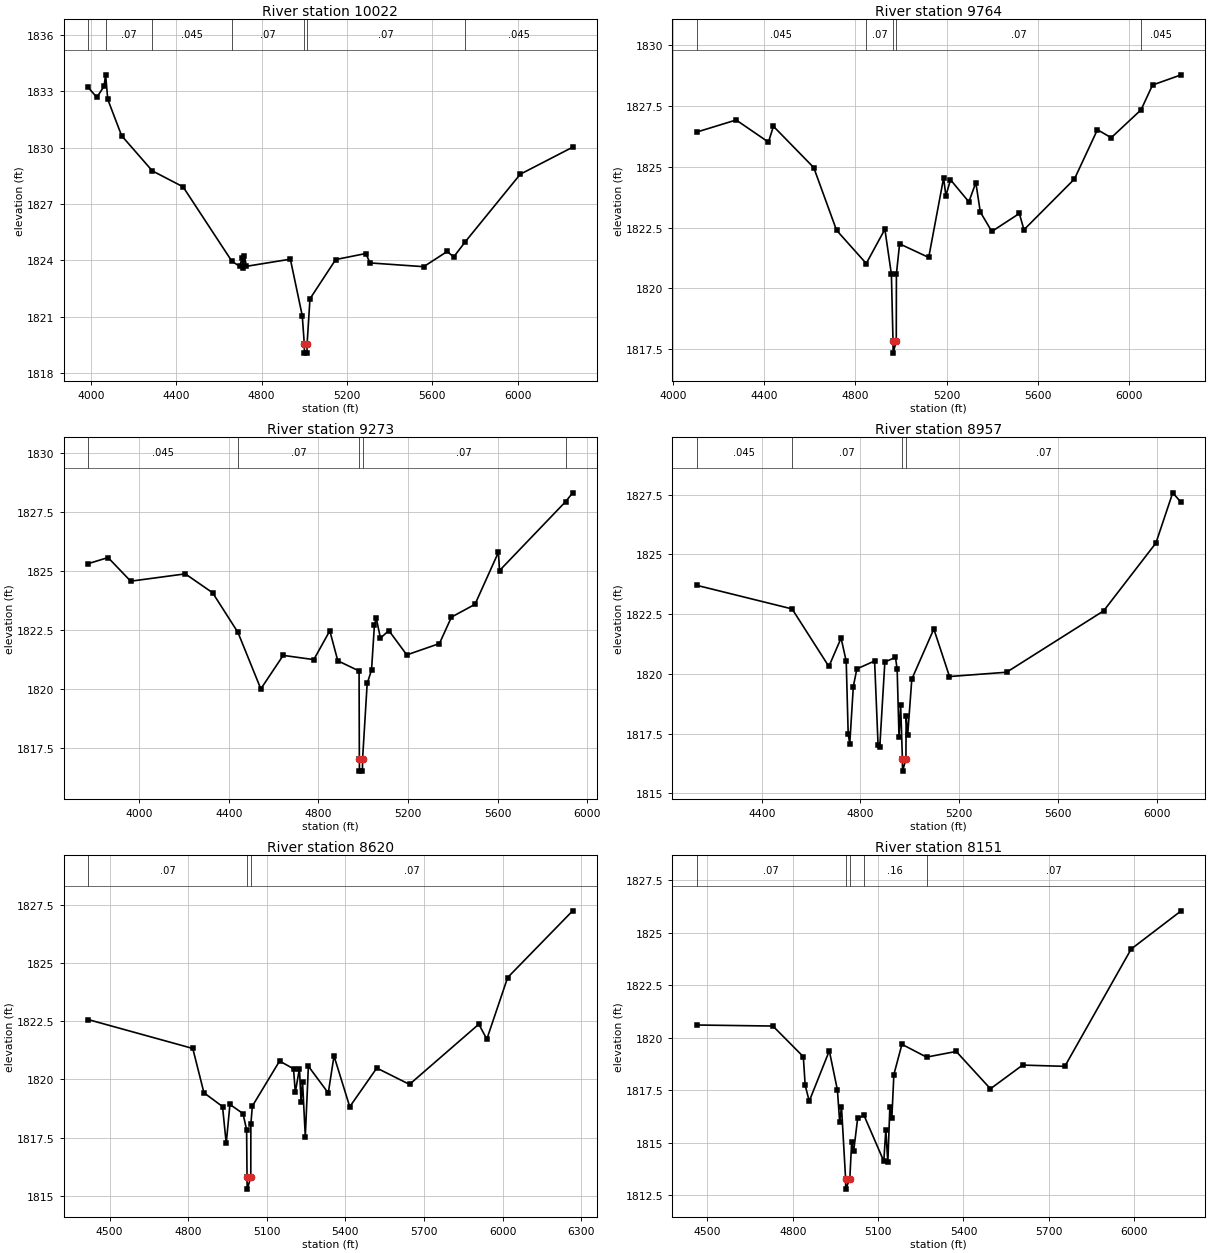
Type RM Length L Ch R = 1 ,10022   ,258,258,258
BEGIN DESCRIPTION:
Elm 01 30 10022.37
END DESCRIPTION:
XS GIS Cut Line= 3
      1545765.07      6823080.86      1546739.05      6822836.06
      1547999.42      6822700.65
#Sta/Elev= 30
    3986 1833.22  4027.2 1832.68  4061.3 1833.27  4068.3 1833.88  4078.7 1832.57
  4143.5 1830.64  4287.3 1828.77  4431.5 1827.92  4659.7 1823.97  4697.4 1823.68
  4707.7 1824.13  4714.3 1823.58  4719.4 1824.25  4728.3 1823.69  4934.5 1824.07
  4990.3 1821.06  4999.7 1819.57  5000.2 1819.07  5012.5 1819.07    5013 1819.57
  5026.4 1821.96  5147.1 1824.05  5287.9 1824.37    5308 1823.87  5559.5 1823.67
  5669.7 1824.48  5700.3 1824.19  5755.4 1825.01  6012.1 1828.59  6257.9 1830.03
#Mann= 7 ,-1 , 0
    3986    .045       0  4068.3     .07       0  4287.3    .045       0
  4659.7     .07       0  4999.7     .07       0    5013     .07       0
  5755.4    .045       0
Bank Sta=4999.7,5013
XS Rating Curve= 0 ,0
Exp/Cntr=0.3,0.1

Type RM Length L Ch R = 1 ,9764    ,491,491,491
BEGIN DESCRIPTION:
Elm 01 30 9764.34
END DESCRIPTION:
XS GIS Cut Line= 3
      1546145.27      6823643.38      1546963.01      6822950.65
      1548009.86      6822825.65
#Sta/Elev= 30
  4102.7 1826.43  4276.4 1826.93  4418.1 1826.02  4440.1 1826.67  4616.9 1824.97
  4716.9 1822.39  4847.2 1821.02  4928.9 1822.43  4957.5 1820.58  4964.6 1817.83
  4965.1 1817.33  4978.9 1817.83  4979.5 1820.59  4993.5 1821.83  5121.2 1821.27
  5186.5 1824.54  5196.6 1823.81  5216.7 1824.47  5297.3 1823.56  5327.9 1824.35
  5347.6 1823.14    5398 1822.34  5518.8 1823.08    5539 1822.41  5760.5  1824.5
  5861.3 1826.53  5921.7  1826.2  6052.8 1827.35    6103 1828.37  6228.7 1828.79
#Mann= 5 ,-1 , 0
  4102.7    .045       0  4847.2     .07       0  4964.6     .07       0
  4978.9     .07       0  6052.8    .045       0
Bank Sta=4964.6,4978.9
XS Rating Curve= 0 ,0
Exp/Cntr=0.3,0.1

Type RM Length L Ch R = 1 ,9273    ,316,316,316
BEGIN DESCRIPTION:
Elm 01 30 9273.49
END DESCRIPTION:
XS GIS Cut Line= 3
      1546145.27      6823893.37      1547140.09      6823190.23
      1548040.55      6822903.96
#Sta/Elev= 30
    3772 1825.32  3861.4 1825.58  3962.4 1824.58  4206.1 1824.89    4328 1824.09
  4441.2 1822.41  4543.2 1820.02  4643.1 1821.44  4779.7 1821.26  4851.1 1822.48
  4886.8 1821.21  4981.7 1820.78    4983 1817.04  4983.5 1816.54  4996.8 1816.54
  4997.3 1817.04  5017.9 1820.25  5037.4 1820.82  5050.1 1822.71  5058.3 1823.02
  5077.1 1822.17  5114.6 1822.49  5194.8 1821.46  5340.3 1821.94  5394.1 1823.06
  5499.1  1823.6  5603.5  1825.8  5608.7 1825.03  5903.9 1827.95  5935.1 1828.32
#Mann= 5 ,-1 , 0
    3772    .045       0  4441.2     .07       0    4983     .07       0
  4997.3     .07       0  5903.9    .035       0
Bank Sta=4983,4997.3
XS Rating Curve= 0 ,0
Exp/Cntr=0.3,0.1

Type RM Length L Ch R = 1 ,8957    ,337,337,337
BEGIN DESCRIPTION:
Elm 01 30 8956.58
END DESCRIPTION:
XS GIS Cut Line= 3
      1546384.88      6823992.31      1547061.96      6823440.23
       1548091.6      6823081.42
#Sta/Elev= 30
  4135.7 1823.71  4522.9 1822.72    4672 1820.31  4721.5  1821.5  4742.3 1820.53
  4750.3 1817.48  4756.7 1817.08  4771.1 1819.47  4785.4 1820.21  4857.3 1820.54
  4871.3 1817.04  4878.1 1816.92  4898.9  1820.5    4942 1820.69  4948.7 1820.19
  4956.3 1817.34  4962.8 1818.71    4970 1816.43  4970.5 1815.93  4984.3 1816.43
  4985.1 1818.24  4991.5 1817.46  5008.1 1819.78  5097.3 1821.88  5160.8 1819.89
  5392.2 1820.07  5785.6 1822.64  5997.4 1825.48  6065.4 1827.58  6099.7 1827.18
#Mann= 4 ,-1 , 0
  4135.7    .045       0  4522.9     .07       0    4970     .07       0
  4984.3     .07       0
Bank Sta=4970,4984.3
XS Rating Curve= 0 ,0
Exp/Cntr=0.3,0.1

Type RM Length L Ch R = 1 ,8620    ,469,469,469
BEGIN DESCRIPTION:
Elm 01 30 8619.62
END DESCRIPTION:
XS GIS Cut Line= 3
      1546624.48      6824132.92       1547020.3      6823700.65
       1548133.7      6823102.32
#Sta/Elev= 30
  4417.5 1822.57  4817.4 1821.33    4860 1819.43  4930.9 1818.84  4945.1 1817.26
  4959.2 1818.93  5009.1 1818.54  5022.9 1817.84  5024.5  1815.8    5025  1815.3
  5038.8  1815.8  5039.1 1818.09  5044.8 1818.86  5148.7 1820.79  5201.9 1820.46
  5208.8 1819.45  5224.6 1820.47  5230.7 1819.04  5236.4  1819.9  5246.9 1817.55
  5258.7 1820.57  5334.6 1819.42  5356.5 1821.01  5416.6 1818.83  5519.8 1820.49
  5644.7 1819.79  5909.3 1822.37  5939.9 1821.73  6019.3 1824.37  6267.6 1827.23
#Mann= 3 ,-1 , 0
  4417.5     .07       0  5024.5     .07       0  5038.8     .07       0
Bank Sta=5024.5,5038.8
XS Rating Curve= 0 ,0
Exp/Cntr=0.3,0.1

Type RM Length L Ch R = 1 ,8151    ,86,86,86
BEGIN DESCRIPTION:
Elm 01 30 8150.62
END DESCRIPTION:
XS GIS Cut Line= 3
      1546864.08      6824304.79       1547270.3      6823971.48
      1548114.07      6823148.54
#Sta/Elev= 30
  4461.5 1820.61  4730.1 1820.56    4837  1819.1  4843.5 1817.74  4857.8 1816.98
  4928.4 1819.38  4956.9 1817.51  4964.8 1815.98  4971.2 1816.72  4985.6 1813.29
  4986.1 1812.79  5000.5 1813.29    5007 1815.05    5014  1814.6  5028.1 1816.17
  5050.5  1816.3    5120 1814.12  5127.1 1815.62  5134.1 1814.06  5141.3  1816.7
  5148.2 1816.17  5155.4 1818.25  5183.7 1819.69  5270.2 1819.08  5374.6 1819.35
  5494.9 1817.57  5608.1  1818.7  5756.5 1818.64  5989.8 1824.23  6165.6 1826.05
#Mann= 5 ,-1 , 0
  4461.5     .07       0  4985.6     .07       0  5000.5     .07       0
  5050.5     .16       0  5270.2     .07       0
Bank Sta=4985.6,5000.5
XS Rating Curve= 0 ,0
Exp/Cntr=0.3,0.1

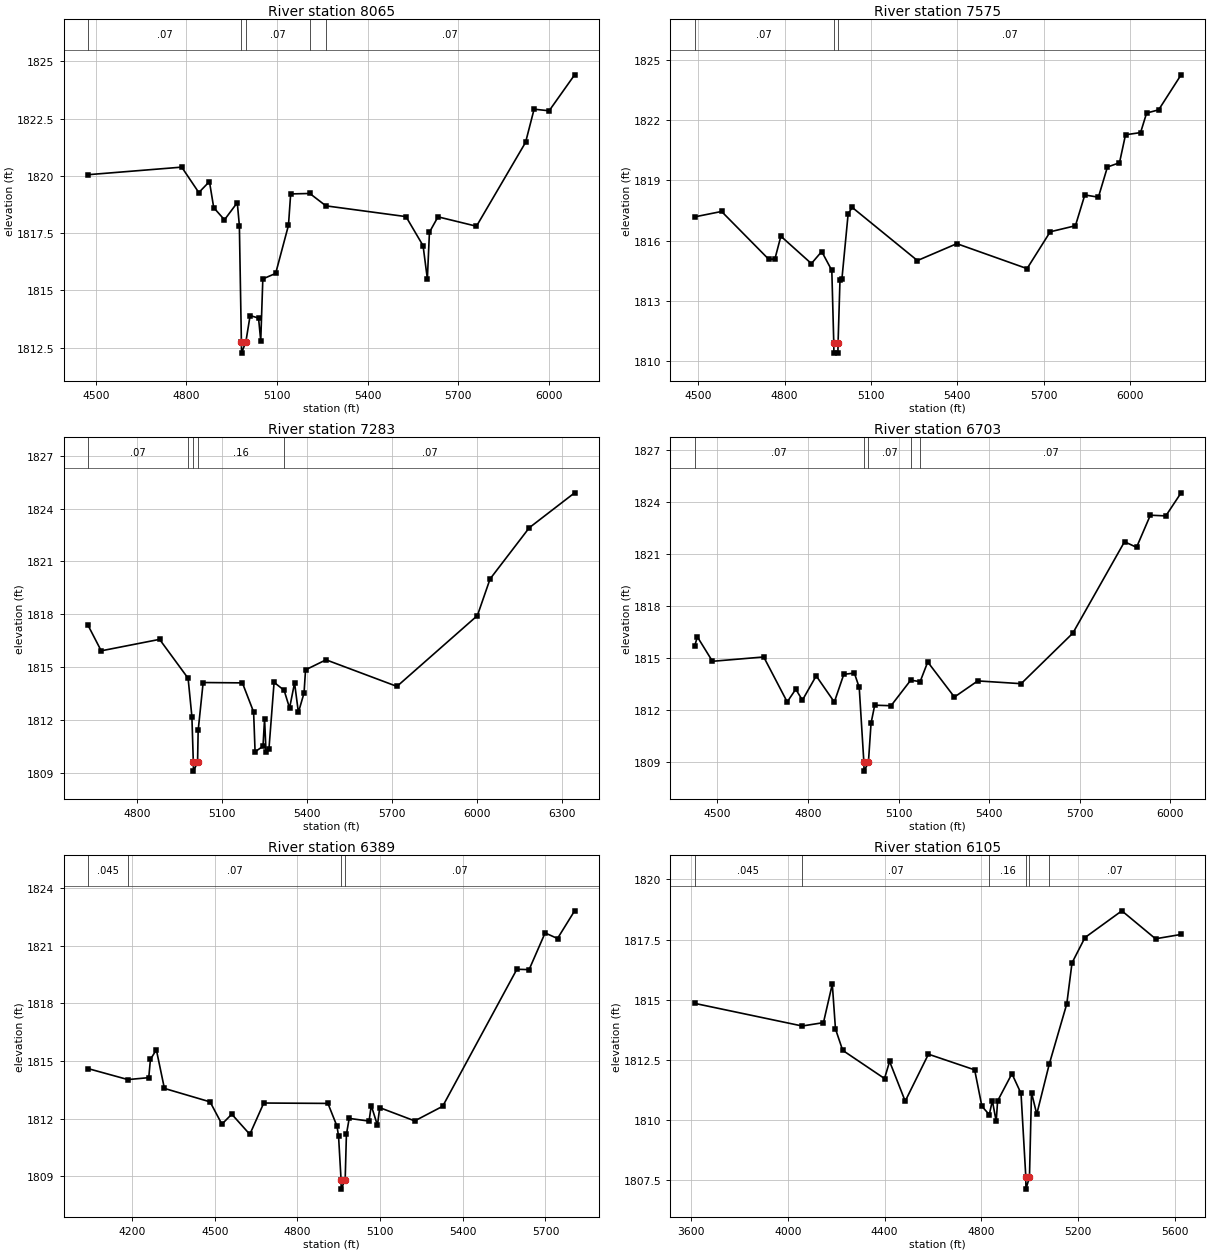
Type RM Length L Ch R = 1 ,8065    ,490,490,490
BEGIN DESCRIPTION:
Elm 01 30 8065.47
END DESCRIPTION:
XS GIS Cut Line= 2
      1546935.25      6824396.44      1548105.36      6823288.83
#Sta/Elev= 30
  4474.4 1820.05  4784.4 1820.38    4841 1819.27  4876.2 1819.75  4890.4 1818.61
    4926 1818.08  4968.4 1818.83  4975.3 1817.83    4982 1812.76  4982.5 1812.26
  4996.9 1812.76  5010.9  1813.9  5038.8 1813.79  5046.1  1812.8    5053  1815.5
  5095.5 1815.74  5137.9 1817.84  5145.2 1819.21  5208.6 1819.23  5261.9 1818.69
  5527.1 1818.22  5583.7 1816.95  5597.9  1815.5  5604.8 1817.54  5633.1 1818.21
  5760.5  1817.8  5923.1 1821.46  5951.4 1822.91  6001.2 1822.84  6085.6 1824.41
#Mann= 5 ,-1 , 0
  4474.4     .07       0    4982     .07       0  4996.9     .07       0
  5208.6     .16       0  5261.9     .07       0
Bank Sta=4982,4996.9
XS Rating Curve= 0 ,0
Exp/Cntr=0.3,0.1

Type RM Length L Ch R = 1 ,7575    ,292,292,292
BEGIN DESCRIPTION:
Elm 01 30 7575.11
END DESCRIPTION:
XS GIS Cut Line= 4
       1547280.5      6824733.94      1547386.63       6824663.8
      1547869.27      6824129.08      1548119.27      6823323.53
#Sta/Elev= 30
  4487.2 1817.18    4581 1817.45  4744.5 1815.08  4766.2 1815.08  4787.1 1816.22
  4893.2 1814.86  4929.1 1815.46  4964.2 1814.52    4971 1810.91  4971.5 1810.41
  4985.4 1810.41  4985.9 1810.91  4992.6 1814.04  4999.4 1814.11    5021 1817.34
  5035.2 1817.65  5261.7 1815.01  5398.7 1815.85  5642.8 1814.61  5723.3 1816.44
  5810.9 1816.74  5843.5 1818.27  5890.8 1818.16  5922.2 1819.66  5964.1 1819.87
    5985 1821.26  6037.4 1821.37  6058.3 1822.34  6100.2  1822.5  6178.2 1824.24
#Mann= 3 ,-1 , 0
  4487.2     .07       0    4971     .07       0  4985.9     .07       0
Bank Sta=4971,4985.9
XS Rating Curve= 0 ,0
Exp/Cntr=0.3,0.1

Type RM Length L Ch R = 1 ,7283    ,580,580,580
BEGIN DESCRIPTION:
Elm 01 30 7283.4
END DESCRIPTION:
XS GIS Cut Line= 3
      1547527.48      6824834.65      1547820.66       6824601.3
      1548195.19      6823311.28
#Sta/Elev= 30
  4626.5 1817.36  4672.7 1815.92  4878.9 1816.57  4979.6 1814.36    4993 1812.18
    4998 1809.59  4998.5 1809.09    5013 1809.59  5015.1  1811.4  5032.7 1814.12
  5171.3  1814.1  5210.9 1812.45  5216.1 1810.19  5244.1  1810.5  5249.6 1812.07
  5254.8 1810.17    5265 1810.33  5283.2 1814.13  5318.6 1813.68  5337.9 1812.67
  5355.5  1814.1  5369.1 1812.42    5389 1813.53  5394.3 1814.84  5466.6 1815.41
  5717.1  1813.9  6001.1 1817.92  6045.9    1820  6184.5 1822.91  6344.5 1824.89
#Mann= 5 ,-1 , 0
  4626.5     .07       0  4979.6     .16       0    4998     .07       0
    5013     .16       0  5318.6     .07       0
Bank Sta=4998,5013
XS Rating Curve= 0 ,0
Exp/Cntr=0.3,0.1

Type RM Length L Ch R = 1 ,6703    ,314,314,314
BEGIN DESCRIPTION:
Elm 01 30 6702.58
END DESCRIPTION:
XS GIS Cut Line= 3
      1547729.98      6824906.26      1547983.86      6824677.69
      1548522.06      6823528.37
#Sta/Elev= 30
  4424.5 1815.67  4433.7 1816.22  4483.7 1814.81  4653.4 1815.06  4731.1 1812.47
  4759.5  1813.2  4781.5 1812.57  4827.1 1813.97  4887.2 1812.46  4918.5 1814.06
  4953.5 1814.13  4969.6  1813.3    4985 1808.98  4985.5 1808.48    5000 1808.98
  5008.7 1811.24  5020.8 1812.28  5074.9 1812.25    5140 1813.72  5171.3 1813.64
  5196.4 1814.77  5284.7 1812.75    5362 1813.68  5505.6 1813.52  5676.7 1816.43
  5847.9  1821.7  5887.7 1821.38  5933.4 1823.23  5984.6 1823.19  6035.2 1824.52
#Mann= 5 ,-1 , 0
  4424.5     .07       0    4985     .07       0    5000     .07       0
    5140     .16       0  5171.3     .07       0
Bank Sta=4985,5000
XS Rating Curve= 0 ,0
Exp/Cntr=0.3,0.1

Type RM Length L Ch R = 1 ,6389    ,284,284,284
BEGIN DESCRIPTION:
Elm 01 30 6389.35
END DESCRIPTION:
XS GIS Cut Line= 3
      1547681.68      6825070.23      1548251.22      6824674.22
      1548744.25      6823722.87
#Sta/Elev= 30
  4040.5 1814.61  4184.9 1814.04  4260.5 1814.14  4266.6 1815.09  4288.1 1815.59
  4317.3 1813.58    4483 1812.88  4525.9 1811.72  4561.7 1812.24  4627.2 1811.19
  4677.8 1812.82  4910.6  1812.8  4943.6 1811.61  4949.2 1811.09  4958.2 1808.84
  4958.7 1808.34  4973.2 1808.84  4977.7 1811.19  4987.8 1812.02  5059.9 1811.88
  5067.8 1812.69  5090.3 1811.66  5098.5 1812.58  5225.5 1811.89  5326.9 1812.65
  5596.2 1819.78  5640.5 1819.76  5698.6 1821.67  5743.6 1821.38  5805.7 1822.82
#Mann= 4 ,-1 , 0
  4040.5    .045       0  4184.9     .07       0  4958.2     .07       0
  4973.2     .07       0
Bank Sta=4958.2,4973.2
XS Rating Curve= 0 ,0
Exp/Cntr=0.3,0.1

Type RM Length L Ch R = 1 ,6105    ,537,537,537
BEGIN DESCRIPTION:
Elm 01 30 6105.28
END DESCRIPTION:
XS GIS Cut Line= 3
      1547466.53      6825261.01      1548150.52       6824788.8
      1549178.27      6824208.96
#Sta/Elev= 30
  3614.8 1814.85  4059.6 1813.91  4147.6 1814.05  4184.1 1815.65  4197.2 1813.79
    4227  1812.9    4400 1811.73    4421 1812.44  4485.5 1810.79  4581.5 1812.74
  4772.6 1812.09  4802.5 1810.58    4833 1810.23  4845.8 1810.81  4861.7 1809.95
  4867.5  1810.8  4926.7 1811.93  4964.3 1811.11  4984.1 1807.64  4984.6 1807.14
  4999.2 1807.64  5007.6 1811.15  5029.3 1810.25  5080.8 1812.32  5153.5 1814.83
  5175.1 1816.53  5228.6 1817.58  5381.1 1818.69  5520.3 1817.53    5626 1817.71
#Mann= 6 ,-1 , 0
  3614.8    .045       0  4059.6     .07       0    4833     .16       0
  4984.1     .07       0  4999.2     .16       0  5080.8     .07       0
Bank Sta=4984.1,4999.2
XS Rating Curve= 0 ,0
Exp/Cntr=0.3,0.1

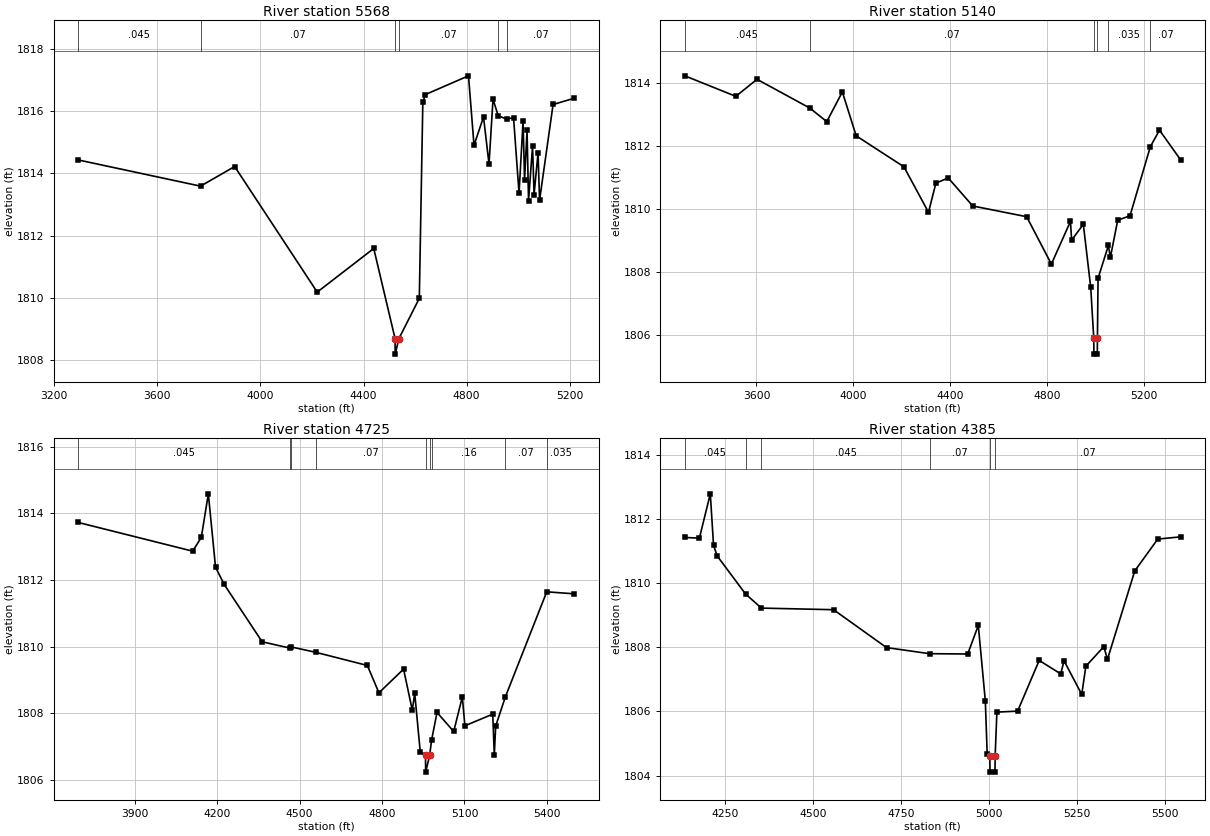
Type RM Length L Ch R = 1 ,5568    ,428,428,428
BEGIN DESCRIPTION:
Elm 01 30 5.0
END DESCRIPTION:
XS GIS Cut Line= 4
      1547463.97      6825284.64      1548113.66      6824864.19
      1548771.29      6824814.84      1549191.58      6824561.67
#Sta/Elev= 30
  3293.2 1814.43  3767.4 1813.59  3899.8 1814.22  4220.2 1810.19  4439.5 1811.59
  4522.2  1808.7  4522.7  1808.2  4537.3  1808.7  4616.3 1809.99    4630 1816.28
    4640 1816.53  4807.2 1817.13  4828.6  1814.9  4865.5 1815.81  4886.8  1814.3
  4902.3 1816.38  4922.4 1815.85  4955.4 1815.74    4982 1815.79  5003.3 1813.36
  5018.9 1815.67  5024.7  1813.8  5034.4 1815.38  5040.2 1813.12  5055.8 1814.88
  5061.6 1813.32  5077.1 1814.66    5083 1813.14  5135.4 1816.21  5217.2 1816.41
#Mann= 6 ,-1 , 0
  3293.2    .045       0  3767.4     .07       0  4522.2     .07       0
  4537.3     .07       0  4922.4     .16       0  4955.4     .07       0
Bank Sta=4522.2,4537.3
XS Rating Curve= 0 ,0
Exp/Cntr=0.3,0.1

Type RM Length L Ch R = 1 ,5140    ,415,415,415
BEGIN DESCRIPTION:
Elm 01 30 5140.31
END DESCRIPTION:
XS GIS Cut Line= 3
       1547445.7      6825320.03      1548067.19      6824910.33
      1549350.94      6825128.92
#Sta/Elev= 30
  3304.3 1814.22    3515 1813.57  3602.3 1814.11  3820.2  1813.2  3890.3 1812.77
  3954.6 1813.71  4011.8 1812.32  4208.8 1811.34  4310.2  1809.9  4340.6 1810.82
  4391.3 1810.99  4492.8  1810.1  4715.4 1809.76  4817.4 1808.26  4896.1 1809.61
  4901.1 1809.02  4949.3 1809.52  4979.7 1807.53  4992.4 1805.91  4992.9 1805.41
    5007 1805.41  5007.5 1805.91  5010.1 1807.81  5052.8 1808.85  5060.8 1808.47
  5091.3 1809.65    5142 1809.79    5226 1811.98  5263.7  1812.5  5350.9 1811.56
#Mann= 6 ,-1 , 0
  3304.3    .045       0  3820.2     .07       0  4992.4     .07       0
  5007.5     .07       0  5052.8    .035       0    5226     .07       0
Bank Sta=4992.4,5007.5
XS Rating Curve= 0 ,0
Exp/Cntr=0.3,0.1

Type RM Length L Ch R = 1 ,4725    ,340,340,340
BEGIN DESCRIPTION:
Elm 01 30 4718.51
END DESCRIPTION:
XS GIS Cut Line= 3
      1547490.77      6825313.12      1548060.25      6825122.14
      1549247.17      6825320.92
#Sta/Elev= 30
    3695 1813.73  4110.8 1812.87  4142.4 1813.28    4168 1814.59  4194.2 1812.39
  4225.8 1811.87  4363.9 1810.15  4465.8 1809.96  4467.5    1810  4561.4 1809.83
  4746.6 1809.44  4788.7 1808.62  4878.4 1809.33  4910.1  1808.1    4919  1808.6
  4939.2 1806.84  4958.2 1806.74  4958.7 1806.24  4973.3 1806.74  4980.1 1807.19
  5000.1 1808.03  5060.9 1807.46  5092.2  1808.5  5101.5 1807.63  5202.9 1807.98
  5208.5 1806.75  5213.5 1807.62  5248.9  1808.5  5399.3 1811.65  5499.1 1811.59
#Mann= 9 ,-1 , 0
    3695    .045       0  4465.8     .07       0  4467.5    .045       0
  4561.4     .07       0  4958.2     .07       0  4973.3     .07       0
  4980.1     .16       0  5248.9     .07       0  5399.3    .035       0
Bank Sta=4958.2,4973.3
XS Rating Curve= 0 ,0
Exp/Cntr=0.3,0.1

Type RM Length L Ch R = 1 ,4385    ,571,571,571
BEGIN DESCRIPTION:
Elm 01 30 4384.75
END DESCRIPTION:
XS GIS Cut Line= 3
      1547793.65      6825447.38      1548650.52      6825517.97
       1549188.7      6825406.86
#Sta/Elev= 30
    4135 1811.42  4176.5  1811.4  4207.5 1812.78  4216.6 1811.19  4226.7 1810.85
  4307.6 1809.66  4352.8 1809.22  4557.8 1809.17  4708.3 1807.99  4830.7  1807.8
  4939.2 1807.79  4969.2 1808.68  4989.2 1806.33  4994.5 1804.67    5002 1804.61
  5002.5 1804.11  5016.6 1804.11  5017.1 1804.61  5022.1 1805.98    5081 1806.01
  5142.3 1807.59  5203.6 1807.17  5212.9 1807.58  5263.2 1806.53    5275 1807.41
  5326.1 1808.02  5336.3 1807.62    5414 1810.38  5479.3 1811.37  5544.3 1811.44
#Mann= 6 ,-1 , 0
    4135    .045       0  4307.6     .07       0  4352.8    .045       0
  4830.7     .07       0    5002     .07       0  5017.1     .07       0
Bank Sta=5002,5017.1
XS Rating Curve= 0 ,0
Exp/Cntr=0.3,0.1