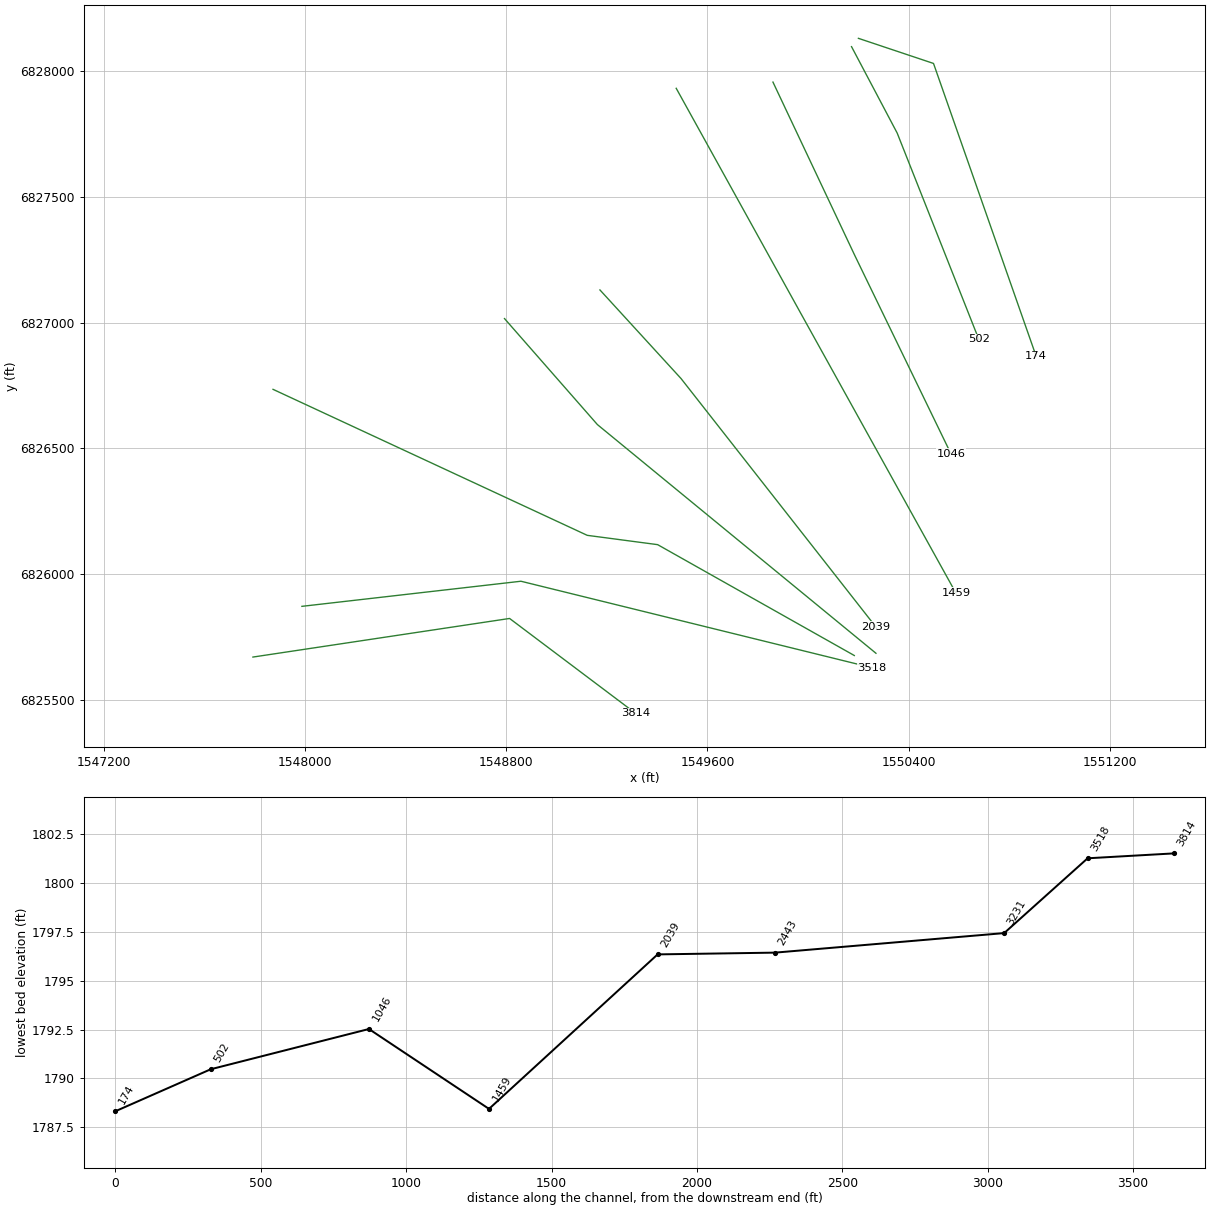
HEC-RAS study Elm 01 30.prj: Elm 01 30 Base Level Engineering

--- Elm 01 30.g01 (geometry) --- (continued)

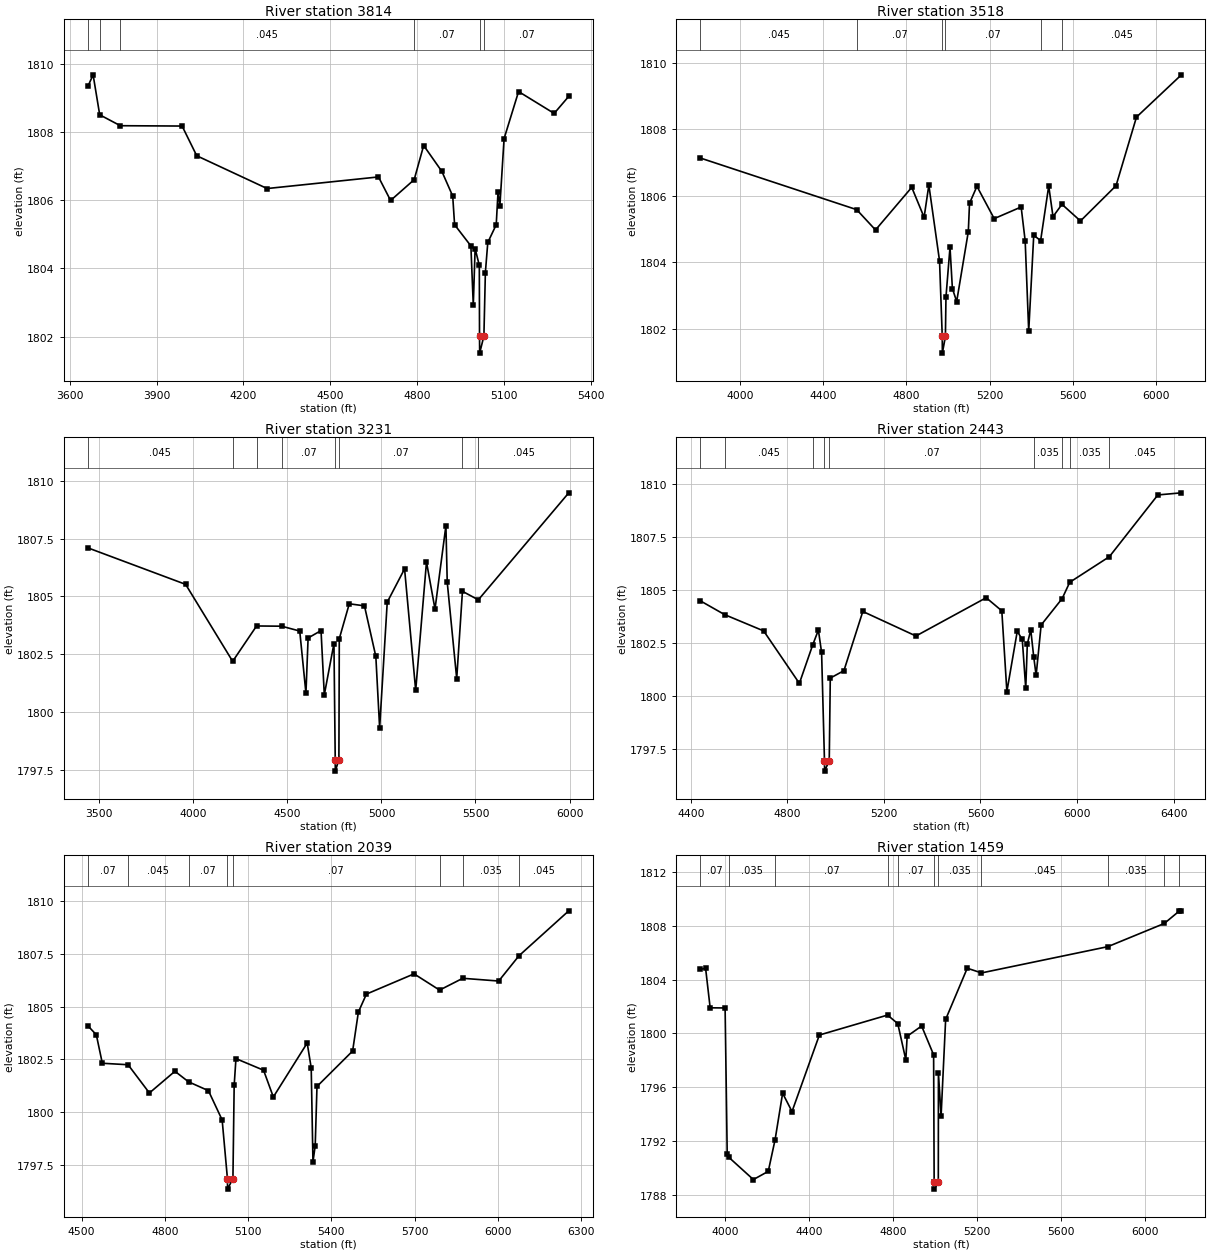
Type RM Length L Ch R = 1 ,3814    ,296,296,296
BEGIN DESCRIPTION:
Elm 01 30 3782.44
END DESCRIPTION:
XS GIS Cut Line= 3
      1547793.44      6825670.09      1548813.72      6825823.53
      1549314.92      6825446.21
#Sta/Elev= 30
  3663.1 1809.33  3681.3 1809.67    3704  1808.5  3775.2 1808.18  3988.3 1808.17
  4038.8  1807.3  4281.5 1806.34  4665.8 1806.68  4707.5 1805.99  4788.9  1806.6
  4821.6  1807.6  4884.5 1806.84  4921.8 1806.12  4928.3 1805.28  4984.5 1804.66
  4992.8 1802.92  4999.1 1804.58  5013.6 1804.09  5014.3 1802.02  5014.8 1801.52
  5029.4 1802.02  5034.5 1803.88  5042.8 1804.76  5071.9 1805.28  5078.2 1806.25
  5084.5 1805.83    5099  1807.8    5149 1809.18  5271.8 1808.54  5322.2 1809.04
#Mann= 6 ,-1 , 0
  3663.1    .045       0    3704     .07       0  3775.2    .045       0
  4788.9     .07       0  5014.3     .07       0  5029.4     .07       0
Bank Sta=5014.3,5029.4
XS Rating Curve= 0 ,0
Exp/Cntr=0.3,0.1

Type RM Length L Ch R = 1 ,3518    ,287,287,287
BEGIN DESCRIPTION:
Elm 01 30 3518.057
END DESCRIPTION:
XS GIS Cut Line= 3
      1547988.11       6825871.7      1548858.84      6825971.48
      1550254.71      6825627.72
#Sta/Elev= 30
    3809 1807.13  4560.8 1805.58  4651.4 1804.97  4825.7 1806.25  4885.2 1805.35
    4908 1806.32  4959.5 1804.04  4972.5 1801.77    4973 1801.27  4987.7 1801.77
  4990.4 1802.96  5009.8 1804.45  5021.3 1803.21  5041.9 1802.82  5097.9 1804.92
  5103.7 1805.77  5139.4 1806.28  5222.4 1805.31  5352.1 1805.66  5371.5 1804.64
  5388.5 1801.93  5412.7 1804.81  5445.8 1804.65  5484.8 1806.29  5505.4 1805.37
  5548.5 1805.74  5637.5 1805.24  5808.7  1806.3    5907 1808.36    6123 1809.63
#Mann= 6 ,-1 , 0
    3809    .045       0  4560.8     .07       0  4972.5     .07       0
  4987.7     .07       0  5445.8    .035       0  5548.5    .045       0
Bank Sta=4972.5,4987.7
XS Rating Curve= 0 ,0
Exp/Cntr=0.3,0.1

Type RM Length L Ch R = 1 ,3231    ,788,788,788
BEGIN DESCRIPTION:
Elm 01 30 1.0
END DESCRIPTION:
XS GIS Cut Line= 4
      1547873.33      6826734.33      1549122.46      6826153.96
      1549402.29      6826116.93      1550183.99      6825676.27
#Sta/Elev= 30
    3439  1807.1  3958.9 1805.52    4209 1802.19  4336.1 1803.72  4469.4 1803.71
  4565.6  1803.5  4598.6 1800.81  4610.1  1803.2  4678.8 1803.52  4696.2 1800.74
  4747.5 1802.96  4754.3 1797.94  4754.8 1797.44  4773.8 1797.94  4775.9 1803.17
    4829 1804.68  4909.7 1804.59  4970.2  1802.4  4990.4 1799.31  5030.8 1804.75
    5123 1806.19  5182.1 1800.93  5239.5 1806.49  5284.8 1804.45  5342.8 1808.06
  5349.8 1805.61  5400.2 1801.44  5430.7 1805.22    5515 1804.85    5996 1809.48
#Mann= 8 ,-1 , 0
    3439    .045       0    4209     .07       0  4336.1    .045       0
  4469.4     .07       0  4754.3     .07       0  4773.8     .07       0
  5430.7    .035       0    5515    .045       0
Bank Sta=4754.3,4773.8
XS Rating Curve= 0 ,0
Exp/Cntr=0.3,0.1

Type RM Length L Ch R = 1 ,2443    ,404,404,404
BEGIN DESCRIPTION:
Elm 01 30 2442.925
END DESCRIPTION:
XS GIS Cut Line= 3
      1548793.49      6827015.61      1549162.86      6826594.17
      1550270.13      6825685.16
#Sta/Elev= 30
  4439.6 1804.49    4540 1803.84  4701.6 1803.07  4849.6 1800.59  4904.6  1802.4
  4928.4 1803.11  4941.7 1802.05  4953.6 1796.94  4954.1 1796.44  4973.4 1796.94
  4977.7 1800.84  5034.2 1801.19  5112.5 1803.99  5332.7 1802.83  5623.8 1804.64
  5688.5 1804.02  5709.5  1800.2  5752.5 1803.05  5773.3 1802.67  5787.7 1800.35
  5794.2 1802.45  5808.5 1803.12  5820.6 1801.86  5830.7 1800.97  5851.5 1803.35
  5938.6  1804.6    5970 1805.37  6134.2 1806.58  6335.2  1809.5  6432.6  1809.6
#Mann= 9 ,-1 , 0
  4439.6     .07       0    4540    .045       0  4904.6     .07       0
  4953.6     .07       0  4973.4     .07       0  5820.6    .035       0
  5938.6    .045       0    5970    .035       0  6134.2    .045       0
Bank Sta=4953.6,4973.4
XS Rating Curve= 0 ,0
Exp/Cntr=0.3,0.1

Type RM Length L Ch R = 1 ,2039    ,580,580,580
BEGIN DESCRIPTION:
Elm 01 30 2039.404
END DESCRIPTION:
XS GIS Cut Line= 3
      1549172.91      6827129.46      1549495.35      6826777.14
      1550270.16      6825789.36
#Sta/Elev= 30
  4522.4  1804.1    4553 1803.67  4574.6 1802.32  4667.4 1802.25  4744.2 1800.91
  4836.2 1801.94  4885.2 1801.44  4956.9 1801.02  5006.4 1799.63  5025.4 1796.85
  5025.9 1796.35  5045.2 1796.85  5049.7 1801.27  5056.1 1802.54  5155.6 1801.99
  5190.8 1800.72  5312.8 1803.28  5327.3  1802.1  5333.6 1797.64  5341.7 1798.41
  5348.1 1801.22  5476.5  1802.9  5497.3 1804.75  5526.2  1805.6  5697.9 1806.56
  5789.9 1805.79  5873.4 1806.35  6002.9 1806.22  6076.1 1807.42  6255.4 1809.55
#Mann= 8 ,-1 , 0
  4522.4     .07       0  4667.4    .045       0  4885.2     .07       0
  5025.4     .07       0  5045.2     .07       0  5789.9    .045       0
  5873.4    .035       0  6076.1    .045       0
Bank Sta=5025.4,5045.2
XS Rating Curve= 0 ,0
Exp/Cntr=0.3,0.1

Type RM Length L Ch R = 1 ,1459    ,413,413,413
BEGIN DESCRIPTION:
Elm 01 30 1528.343
END DESCRIPTION:
XS GIS Cut Line= 3
      1549476.14      6827931.01      1549956.22       6827063.7
      1550588.01      6825924.59
#Sta/Elev= 30
  3881.7 1804.75  3906.3 1804.84  3928.1  1801.9  3999.4 1801.89  4009.4 1791.03
  4015.9 1790.82  4134.2 1789.15  4205.2 1789.76  4237.9 1792.12  4273.7 1795.56
  4318.5  1794.2    4449 1799.88    4774 1801.36  4822.9 1800.73  4861.3 1798.04
  4867.7 1799.79  4936.7 1800.55  4993.9 1798.41  4996.5 1788.94    4997 1788.44
  5016.3 1788.94  5016.8 1797.09  5029.5 1793.85  5051.3 1801.04  5154.3 1804.84
  5222.2 1804.49  5824.9 1806.44  6093.9 1808.16  6165.3 1809.08  6175.6  1809.1
#Mann= 11 ,-1 , 0
  3881.7     .07       0  4015.9    .035       0  4237.9     .07       0
    4774    .045       0  4822.9     .07       0  4996.5     .07       0
  5016.3    .035       0  5222.2    .045       0  5824.9    .035       0
  6093.9    .045       0  6165.3    .035       0
Bank Sta=4996.5,5016.3
XS Rating Curve= 0 ,0
Exp/Cntr=0.3,0.1

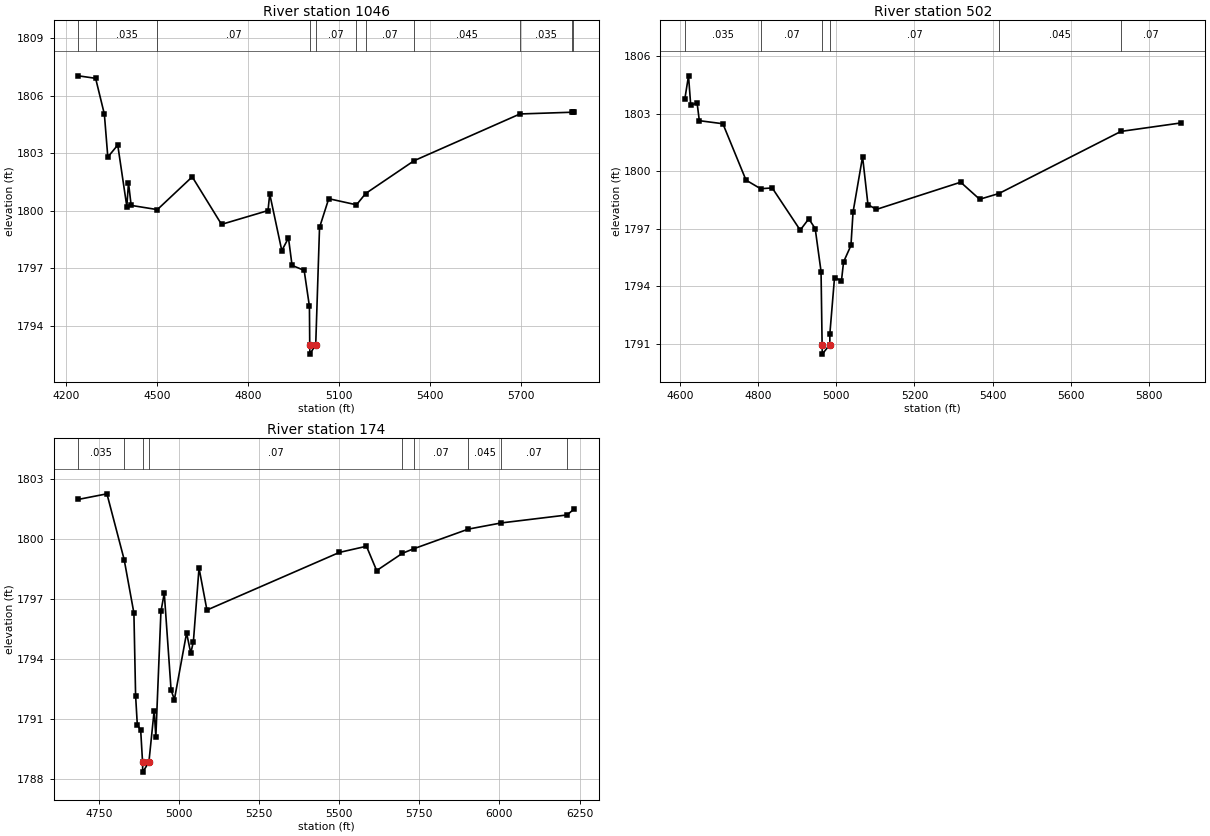
Type RM Length L Ch R = 1 ,1046    ,544,544,544
BEGIN DESCRIPTION:
Elm 01 30 1045.583
END DESCRIPTION:
XS GIS Cut Line= 3
      1549860.66      6827955.76      1550185.37      6827267.84
      1550568.09      6826478.54
#Sta/Elev= 30
  4239.3 1807.05  4296.4 1806.92  4325.3 1805.05  4336.7 1802.81  4369.5 1803.44
  4399.5 1800.23    4405 1801.47  4413.8 1800.29  4500.3 1800.07  4615.5 1801.78
  4712.3  1799.3  4865.9 1800.02  4871.5 1800.89  4911.4 1797.93  4933.5 1798.59
  4945.3 1797.16  4985.3  1796.9  5002.7 1795.02  5003.7 1793.03  5004.2 1792.53
  5023.5 1793.03  5036.1 1799.14  5066.5 1800.64  5158.1 1800.32  5188.4 1800.91
  5348.3 1802.62  5698.1 1805.06  5868.8 1805.15  5872.1 1805.16  5877.2 1805.17
#Mann= 11 ,-1 , 0
  4239.3     .07       0  4296.4    .035       0  4500.3     .07       0
  5003.7     .07       0  5023.5     .07       0  5158.1    .045       0
  5188.4     .07       0  5348.3    .045       0  5698.1    .035       0
  5868.8    .045       0  5872.1    .035       0
Bank Sta=5003.7,5023.5
XS Rating Curve= 0 ,0
Exp/Cntr=0.3,0.1

Type RM Length L Ch R = 1 ,502     ,328,328,328
BEGIN DESCRIPTION:
Elm 01 30 502.356
END DESCRIPTION:
XS GIS Cut Line= 3
      1550173.05      6828096.64      1550354.47      6827753.22
      1550679.04      6826933.11
#Sta/Elev= 30
  4611.6 1803.77  4621.1 1804.99  4626.8 1803.45  4643.1 1803.58  4648.8 1802.65
  4709.2 1802.49  4768.4 1799.55  4805.8  1799.1  4835.6 1799.14  4907.3 1796.94
  4929.3 1797.53  4945.7 1797.02  4960.7 1794.78  4963.4 1790.97  4963.9 1790.47
  4983.2 1790.97  4983.3 1791.54  4995.2 1794.46    5013  1794.3  5018.4 1795.28
  5037.3 1796.14  5042.7 1797.88  5067.1 1800.77  5080.9 1798.27  5102.4 1798.02
  5318.4 1799.44  5367.1 1798.55  5416.5 1798.85  5729.1 1802.09    5882 1802.53
#Mann= 6 ,-1 , 0
  4611.6    .035       0  4805.8     .07       0  4963.4     .07       0
  4983.2     .07       0  5416.5    .045       0  5729.1     .07       0
Bank Sta=4963.4,4983.2
XS Rating Curve= 0 ,0
Exp/Cntr=0.3,0.1

Type RM Length L Ch R = 1 ,174     ,0,0,0
BEGIN DESCRIPTION:
Elm 01 30 173.592
END DESCRIPTION:
XS GIS Cut Line= 3
      1550200.39      6828129.69      1550498.94      6828029.86
      1550906.94      6826866.11
#Sta/Elev= 30
  4685.2    1802  4774.5 1802.28  4828.3 1798.98  4858.7  1796.3    4864 1792.16
  4869.3  1790.7  4879.9 1790.42  4885.7 1788.82  4886.2 1788.32  4905.5 1788.82
  4921.9  1791.4  4927.2  1790.1  4943.1 1796.38  4953.5  1797.3  4974.8 1792.43
  4985.1 1791.96  5023.2  1795.3  5036.2 1794.29  5044.4 1794.86    5062 1798.56
  5086.7 1796.45    5500 1799.34  5584.8 1799.65  5616.6 1798.43  5697.2  1799.3
  5733.2 1799.53  5902.7 1800.51  6005.5 1800.82  6211.1 1801.22  6233.2 1801.52
#Mann= 9 ,-1 , 0
  4685.2    .035       0  4828.3     .07       0  4885.7     .07       0
  4905.5     .07       0  5697.2    .045       0  5733.2     .07       0
  5902.7    .045       0  6005.5     .07       0  6211.1    .035       0
Bank Sta=4885.7,4905.5
XS Rating Curve= 0 ,0
Exp/Cntr=0.3,0.1

Chan Stop Cuts=-1
Use User Specified Reach Order=0
Composite Channel Slope=5