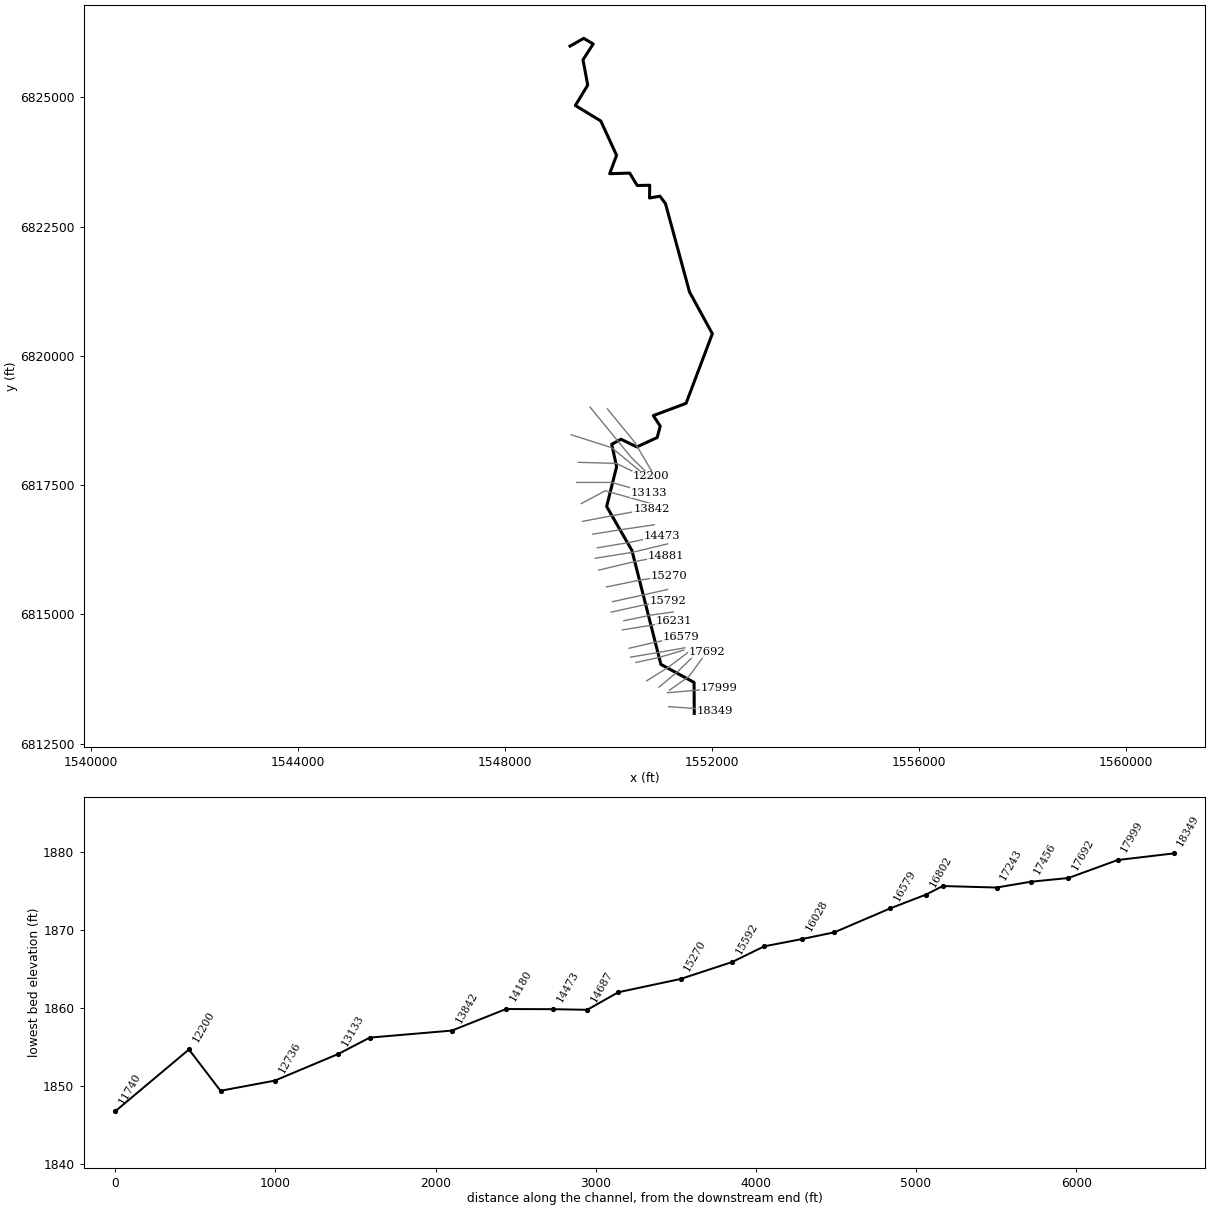
--- Elm 01 31.prj (project) ---

Proj Title=Elm 01 31 Base Level Engineering
Current Plan=p01
Default Exp/Contr=0.3,0.1
English Units
Geom File=g01
Flow File=f01
Plan File=p01
Y Axis Title=Elevation
X Axis Title(PF)=Main Channel Distance
X Axis Title(XS)=Station
BEGIN DESCRIPTION:
Elm 01 31
END DESCRIPTION:
DSS Export Rating Curves= 0
DSS Export Rating Curve Sorted= 0
DSS Export Volume Flow Curves= 0
DXF OffsetX= 0
DXF OffsetY= 0
DXF ScaleX= 1
DXF ScaleY= 10

--- Elm 01 31.p01 (plan) ---

Plan Title=Multiple Run
Program Version=4.10
Short Identifier=Multiple
Geom File=g01
Flow File=f01
Subcritical Flow
K Sum by GR= 0
Std Step Tol= 0.01
Critical Tol= 0.01
Num of Std Step Trials= 20
Max Error Tol= 0.3
Flow Tol Ratio= 0.001
Split Flow NTrial= 30
Split Flow Tol= 0.02
Split Flow Ratio= 0.02
Log Output Level= 0
Friction Slope Method= 1
Unsteady Friction Slope Method= 2
Unsteady Bridges Friction Slope Method= 1
Parabolic Critical Depth
Global Vel Dist= 1 , 1 , 1
Global Log Level= 0
CheckData=True
Encroach Param=-1 ,0,0, 0
BEGIN DESCRIPTION:
Multiple Run
END DESCRIPTION:
Computation Interval=1HOUR
Output Interval=1HOUR
Run HTab= 0
Run UNet= 0
Run PostProcess= 0
Run WQNet= 0
UNET Theta= 1
UNET Theta Warmup= 1
UNET ZTol= 0.02
UNET ZSATol= 0.05
UNET MxIter= 20
UNET MaxInSteps= 0
UNET DtIC= 0
UNET DtMin= 0
UNET MaxCRTS= 20
UNET WFStab= 2
UNET SFStab= 1
UNET WFX= 1
UNET SFX= 1
UNET DSS MLevel= 4
UNET DZMax Abort= 100
UNET Convert EG Bridges= 0
UNET Use Existing IB Tables=-1
UNET Froude Reduction=False
UNET Froude Limit= 1
UNET Froude Power= 10
UNET Time Slicing=0,0, 5
UNET Junction Losses=0
Instantaneous Interval=1HOUR
Write IC File= 0
Write IC File at Sim End=0
Echo Input=False
Echo Parameters=False
Echo Output=False
Write Detailed= 0
WQ AD Non Conservative
WQ ULTIMATE=-1
WQ Max Comp Step=1HOUR
WQ Output Interval=15MIN
WQ Output Selected Increments= 0
WQ Output face flow=0
WQ Output face velocity=0
WQ Output face area=0
WQ Output face dispersion=0
WQ Output cell volume=0
WQ Output cell surface area=0
WQ Output cell continuity=0
WQ Output cumulative cell continuity=0
WQ Output face conc=0
WQ Output face dconc_dx=0
WQ Output face courant=0
WQ Output face peclet=0
WQ Output face adv mass=0
WQ Output face disp mass=0
WQ Output cell mass=0
WQ Output cell source sink temp=0
WQ Output cell source sink nsm=0
WQ Output MaxMinRange=-1
WQ Daily Max Min Mean=-1
WQ Daily Range=0
WQ Daily Time=0
WQ Create Restart=0
WQ Fixed Restart=0
WQ System Summary=0
WQ Use Fixed Temperature=0
Sorting and Armoring Iterations= 10
XS Update Threshold= 0.02
Hydraulics Update Threshold= 0.02
Energy Slope Method= 1
Volume Change Method= 0
XS Weighting Method= 0
Number of US Weighted Cross Sections= 1
Number of DS Weighted Cross Sections= 1
Upstream XS Weight=0.25
Main XS Weight=0.5
Downstream XS Weight=0.25
Number of DS XS's Weighted with US Boundary= 1
Upstream Boundary Weight= 1
Weight of XSs Associated with US Boundary= 0
Number of US XS's Weighted with DS Boundary= 1
Downstream Boundary Weight= 0.5
Weight of XSs Associated with DS Boundary= 0.5
Sediment Output Level= 4
Mass or Volume Output= 0
Output Increment Type= 1
Profile and TS Output Increment= 10
XS Output Flag= 0
XS Output Increment= 10
Disregard all LS=0
Disregard all Conn=0
Disregard all Breaches=0
Disregard all Pumps=0

--- Elm 01 31.f01 (steady flow) ---

Flow Title=Multiple
Number of Profiles=7
Profile Names=10-year,25-year,50-year,1pct_min,100-year,1pct_plu,500-year
River Rch & RM= Elm 01 31,Reach-1,18349
     222     307     376     286     459     632     692
River Rch & RM= Elm 01 31,Reach-1,16028
     346     487     605     466     746    1030    1150
River Rch & RM= Elm 01 31,Reach-1,9334
     444     631     788     609     977    1340    1520
Boundary for River Rch & Prof#=Elm 01 31,Reach-1,1
Up Type=0
Dn Type=3
Dn Slope=0.005
Boundary for River Rch & Prof#=Elm 01 31,Reach-1,2
Up Type=0
Dn Type=3
Dn Slope=0.005
Boundary for River Rch & Prof#=Elm 01 31,Reach-1,3
Up Type=0
Dn Type=3
Dn Slope=0.005
Boundary for River Rch & Prof#=Elm 01 31,Reach-1,4
Up Type=0
Dn Type=3
Dn Slope=0.005
Boundary for River Rch & Prof#=Elm 01 31,Reach-1,5
Up Type=0
Dn Type=3
Dn Slope=0.005
Boundary for River Rch & Prof#=Elm 01 31,Reach-1,6
Up Type=0
Dn Type=3
Dn Slope=0.005
Boundary for River Rch & Prof#=Elm 01 31,Reach-1,7
Up Type=0
Dn Type=3
Dn Slope=0.005

--- Elm 01 31.g01 (geometry) ---

Geom Title=Existing Conditions
Program Version=4.10

River Reach=Elm 01 31       ,Reach-1
Reach XY= 30
        1551655.        6813088.      1551651.46      6813686.54
      1551010.28      6814035.29      1550451.17      6816236.42
      1549962.33       6817087.9      1550154.95      6817858.04
      1550060.39      6818290.44      1550239.78      6818387.76
      1550544.56      6818239.03      1550938.57      6818420.38
      1550996.96      6818641.32      1550863.96      6818844.67
      1551496.87      6819081.92      1552004.41      6820427.39
      1551563.24      6821234.76      1551099.53      6822940.45
      1550992.99      6823086.83      1550790.88      6823051.32
      1550794.68      6823298.18      1550552.69      6823293.08
      1550407.58      6823533.03      1550021.05      6823520.95
      1550154.07      6823877.52      1549849.48      6824540.43
       1549358.1      6824839.65      1549597.17      6825234.73
       1549505.2      6825722.66      1549702.37      6826029.52
      1549520.36      6826138.11        1549255.        6825988.

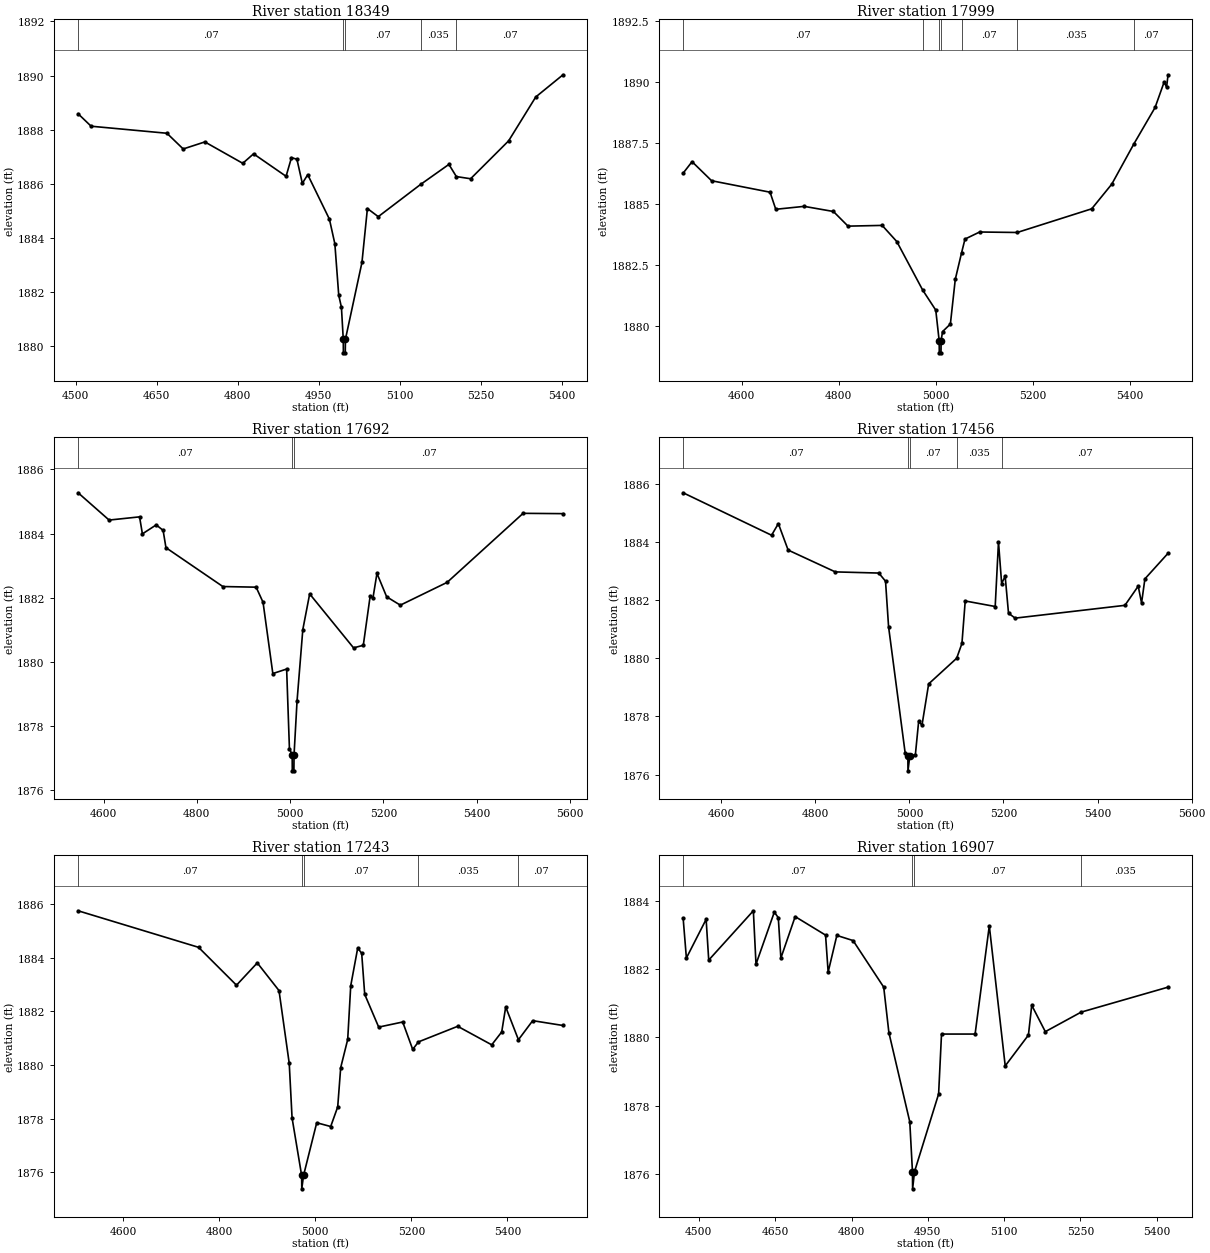
Type RM Length L Ch R = 1 ,18349   ,350,350,350
BEGIN DESCRIPTION:
Elm 01 31 18348.96
END DESCRIPTION:
XS GIS Cut Line= 3
      1551160.98      6813219.36      1551655.08       6813182.2
      1552055.05      6813137.99
#Sta/Elev= 30
  4504.5 1888.59  4528.6 1888.13    4669 1887.87  4699.1 1887.29  4739.2 1887.55
  4809.4 1886.76  4829.4 1887.11  4889.6 1886.28  4899.6 1886.97  4909.7 1886.91
  4919.7 1886.02  4929.7 1886.34  4969.8  1884.7  4979.9 1883.79  4987.1 1881.89
  4992.1 1881.44  4995.5 1880.26  4995.7 1879.76  4999.2 1879.76  4999.5 1880.26
  5030.1  1883.1  5040.2 1885.09  5060.3 1884.79  5138.7 1885.98  5191.1 1886.72
  5204.9 1886.27  5231.3 1886.19  5301.7 1887.59  5351.9 1889.21  5402.4 1890.03
#Mann= 5 ,-1 , 0
  4504.5     .07       0  4995.5     .07       0  4999.5     .07       0
  5138.7    .035       0  5204.9     .07       0
Bank Sta=4995.5,4999.5
XS Rating Curve= 0 ,0
Exp/Cntr=0.3,0.1

Type RM Length L Ch R = 1 ,17999   ,307,307,307
BEGIN DESCRIPTION:
Elm 01 31 17999.25
END DESCRIPTION:
XS GIS Cut Line= 2
      1551136.65      6813486.72      1552131.58      6813573.39
#Sta/Elev= 30
  4479.3 1886.27  4497.7 1886.74  4537.9 1885.96  4658.3 1885.49  4670.1 1884.79
  4728.6 1884.91  4788.8  1884.7  4818.9  1884.1  4889.2 1884.13  4919.3 1883.47
  4972.7 1881.48  4999.6 1880.66  5006.6 1879.41  5006.9 1878.91  5010.4 1878.91
  5010.6 1879.41  5013.6 1879.78  5029.7 1880.09  5039.8 1881.92  5052.9 1883.02
  5059.8 1883.57    5090 1883.86  5167.3 1883.84  5320.8 1884.81  5362.1 1885.82
  5407.7 1887.47  5451.3 1888.96  5469.9    1890    5475 1889.79    5478  1890.3
#Mann= 7 ,-1 , 0
  4479.3     .07       0  4972.7    .035       0  5006.6    .035       0
  5010.6    .035       0  5052.9     .07       0  5167.3    .035       0
  5407.7     .07       0
Bank Sta=5006.6,5010.6
XS Rating Curve= 0 ,0
Exp/Cntr=0.3,0.1

Type RM Length L Ch R = 1 ,17692   ,236,236,236
BEGIN DESCRIPTION:
Elm 01 31 17691.93
END DESCRIPTION:
XS GIS Cut Line= 3
       1551174.8      6813535.31      1551549.83      6813799.22
       1551893.6        6814268.
#Sta/Elev= 30
  4545.4 1885.27  4611.9 1884.42  4677.2 1884.52  4683.3 1883.99  4712.9 1884.27
  4727.7  1884.1  4733.8 1883.56  4855.8 1882.35  4927.2 1882.33    4942 1881.86
    4963 1879.64  4992.6 1879.78  4998.6  1877.3  5004.5 1877.11  5004.7 1876.61
  5008.2 1876.61  5008.5 1877.11  5014.9 1878.78  5027.3 1881.01    5042 1882.12
  5136.1 1880.44    5157 1880.52  5171.6 1882.04  5177.8    1882  5186.3 1882.76
  5207.1 1882.03  5236.4 1881.77  5336.8 1882.48  5499.7 1884.63  5585.3 1884.62
#Mann= 3 ,-1 , 0
  4545.4     .07       0  5004.5     .07       0  5008.5     .07       0
Bank Sta=5004.5,5008.5
XS Rating Curve= 0 ,0
Exp/Cntr=0.3,0.1

Type RM Length L Ch R = 1 ,17456   ,213,213,213
BEGIN DESCRIPTION:
Elm 01 31 17455.93
END DESCRIPTION:
XS GIS Cut Line= 3
      1550973.48      6813594.39      1551344.97      6813903.39
      1551733.84      6814288.79
#Sta/Elev= 30
  4519.1 1885.69  4707.1 1884.23  4721.5 1884.63  4742.3 1883.72  4842.5 1882.97
    4935 1882.93  4949.3 1882.65  4955.8 1881.08  4990.9 1876.76  4996.8 1876.63
    4997 1876.13  5000.8 1876.63  5012.7 1876.68  5019.7 1877.83  5026.8  1877.7
    5041 1879.12  5100.5    1880  5111.7 1880.51  5118.7 1881.97  5182.4 1881.78
  5189.4    1884  5196.1 1882.57  5203.6 1882.82  5210.7 1881.55  5224.8 1881.38
  5458.1 1881.82  5486.4 1882.48  5493.5  1881.9  5500.6 1882.73  5549.8 1883.61
#Mann= 5 ,-1 , 0
  4519.1     .07       0  4996.8     .07       0  5000.8     .07       0
  5100.5    .035       0  5196.1     .07       0
Bank Sta=4996.8,5000.8
XS Rating Curve= 0 ,0
Exp/Cntr=0.3,0.1

Type RM Length L Ch R = 1 ,17243   ,336,336,336
BEGIN DESCRIPTION:
Elm 01 31 17272.36
END DESCRIPTION:
XS GIS Cut Line= 3
      1550738.51      6813719.53      1551144.72      6813972.98
      1551568.37      6814292.45
#Sta/Elev= 30
  4506.3 1885.74    4757 1884.38    4836 1882.97  4879.3  1883.8  4924.5 1882.77
  4945.8 1880.06  4951.7 1878.03  4971.6 1875.89  4971.9 1875.39  4975.6 1875.89
    5003 1877.85  5032.1 1877.71  5046.7 1878.44  5052.9  1879.9  5067.5 1880.95
  5073.8 1882.95  5088.3 1884.35  5096.6 1884.16  5102.9 1882.63    5132 1881.41
    5182  1881.6  5202.8 1880.58  5214.8 1880.86  5296.5 1881.44  5367.3 1880.75
  5388.1 1881.23  5396.4 1882.16  5422.9 1880.94  5452.6 1881.65  5515.7 1881.47
#Mann= 5 ,-1 , 0
  4506.3     .07       0  4971.6     .07       0  4975.6     .07       0
  5214.8    .035       0  5422.9     .07       0
Bank Sta=4971.6,4975.6
XS Rating Curve= 0 ,0
Exp/Cntr=0.3,0.1

Type RM Length L Ch R = 1 ,16907   ,105,105,105
BEGIN DESCRIPTION:
Elm 01 31 17003.62
END DESCRIPTION:
XS GIS Cut Line= 3
      1550529.93      6814072.46      1550974.39      6814169.68
      1551451.79      6814311.52
#Sta/Elev= 30
  4469.1 1883.49  4475.5 1882.32  4514.3 1883.45  4519.4 1882.26  4607.1  1883.7
  4612.3 1882.14  4648.3 1883.66  4656.1  1883.5  4661.2 1882.32  4689.3 1883.53
    4749 1882.99  4754.1 1881.91  4771.2 1882.98  4803.1 1882.83  4863.3 1881.47
  4873.5 1880.14  4914.5 1877.54  4919.8 1876.08  4920.1 1875.58  4923.8 1876.08
  4971.2 1878.35  4976.9  1880.1  5042.9  1880.1  5070.8 1883.26  5102.1 1879.17
  5147.7 1880.07  5154.2 1880.94  5180.9 1880.17  5251.3 1880.74  5422.1 1881.47
#Mann= 4 ,-1 , 0
  4469.1     .07       0  4919.8     .07       0  4923.8     .07       0
  5251.3    .035       0
Bank Sta=4919.8,4923.8
XS Rating Curve= 0 ,0
Exp/Cntr=0.3,0.1

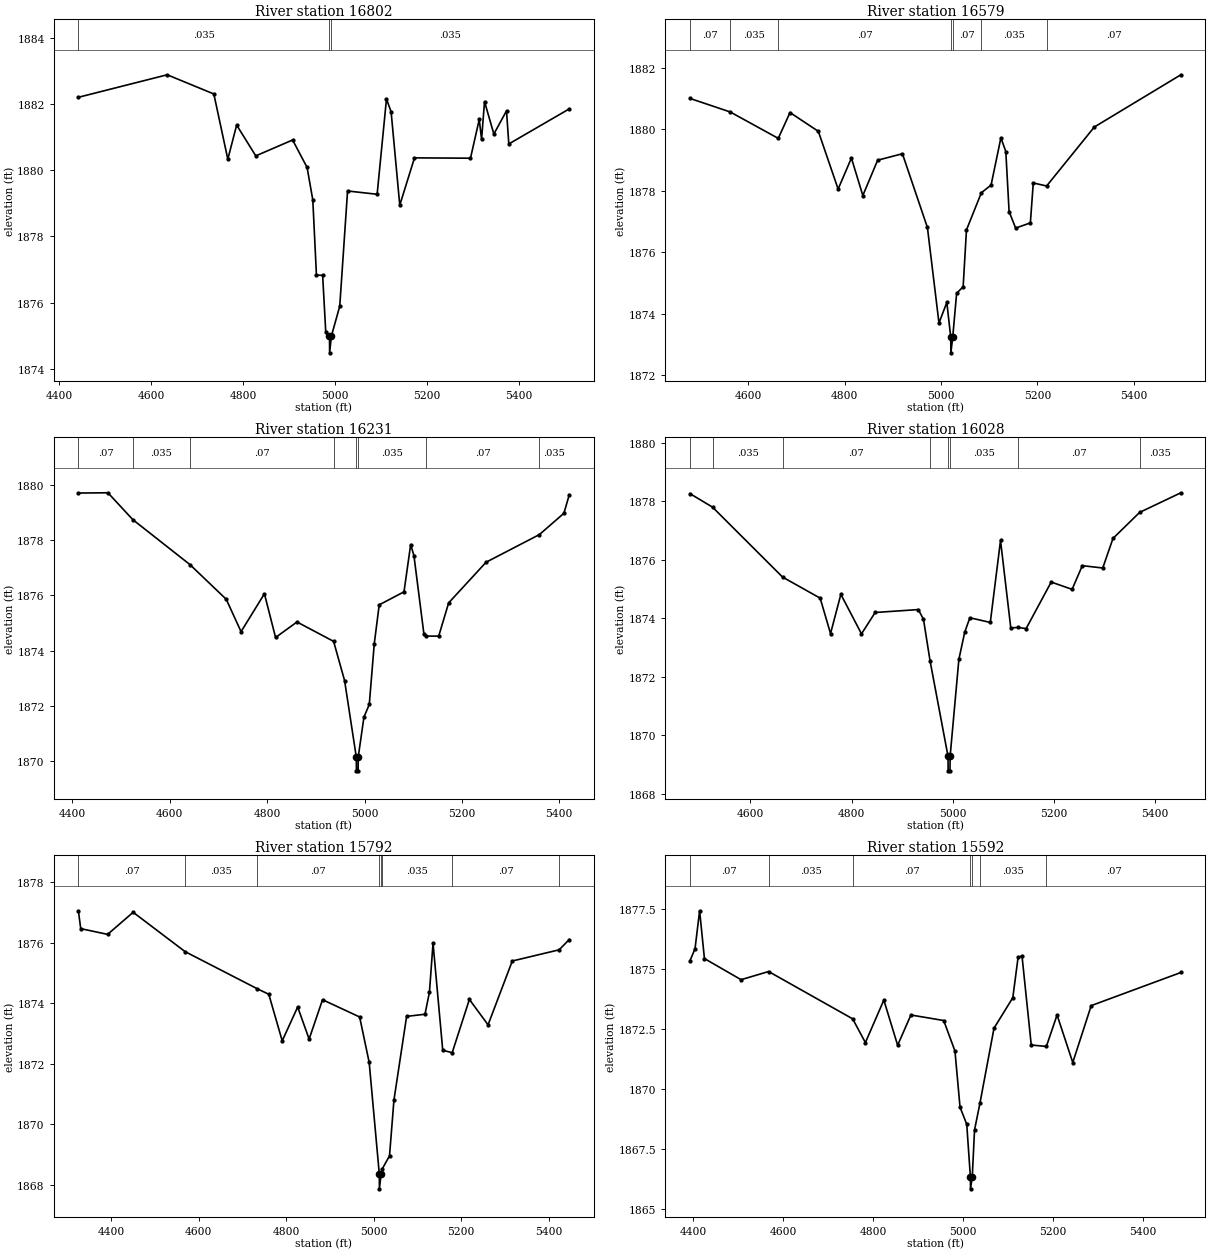
Type RM Length L Ch R = 1 ,16802   ,223,223,223
BEGIN DESCRIPTION:
Elm 01 31 16695.61
END DESCRIPTION:
XS GIS Cut Line= 3
      1550424.51      6814175.77      1550924.46       6814259.1
      1551476.52      6814356.32
#Sta/Elev= 30
  4441.6  1882.2  4634.7 1882.88  4736.1  1882.3  4766.5 1880.33  4785.7 1881.36
  4827.3 1880.43  4907.4 1880.91  4938.9 1880.08  4951.3  1879.1  4959.2 1876.83
  4972.7 1876.82  4979.5  1875.1  4987.6 1874.98  4987.9 1874.48  4991.6 1874.98
  5009.9 1875.89  5026.9 1879.37  5091.2 1879.27  5111.5 1882.15  5121.6 1881.76
  5140.4 1878.94  5172.4 1880.37  5294.2 1880.36  5313.2 1881.53  5318.3 1880.93
  5324.7 1882.07    5345 1881.09  5372.5 1881.79  5377.5 1880.79    5509 1881.85
#Mann= 3 ,-1 , 0
  4441.6    .035       0  4987.6    .035       0  4991.6    .035       0
Bank Sta=4987.6,4991.6
XS Rating Curve= 0 ,0
Exp/Cntr=0.3,0.1

Type RM Length L Ch R = 1 ,16579   ,348,348,348
BEGIN DESCRIPTION:
Elm 01 31 16455.89
END DESCRIPTION:
XS GIS Cut Line= 3
      1550395.48      6814346.31       1550871.2      6814457.43
      1551390.99      6814564.85
#Sta/Elev= 30
  4478.7    1881  4562.2 1880.56    4662  1879.7  4686.4 1880.54  4745.2 1879.93
  4786.3 1878.05  4813.9 1879.06  4837.6 1877.84  4868.4 1878.99  4919.8  1879.2
  4971.7  1876.8  4995.7 1873.69    5012 1874.36  5020.2 1873.22  5020.4 1872.72
  5024.2 1873.22  5032.4 1874.66  5045.9 1874.87  5052.8 1876.72  5083.7 1877.93
  5103.9 1878.18  5124.3 1879.72  5134.5 1879.27  5141.3 1877.32  5154.9 1876.78
  5185.5 1876.95  5191.5 1878.25  5219.2 1878.15  5318.3 1880.07    5498 1881.77
#Mann= 7 ,-1 , 0
  4478.7     .07       0  4562.2    .035       0    4662     .07       0
  5020.2     .07       0  5024.2     .07       0  5083.7    .035       0
  5219.2     .07       0
Bank Sta=5020.2,5024.2
XS Rating Curve= 0 ,0
Exp/Cntr=0.3,0.1

Type RM Length L Ch R = 1 ,16231   ,203,203,203
BEGIN DESCRIPTION:
Elm 01 31 16230.56
END DESCRIPTION:
XS GIS Cut Line= 3
       1550265.1        6814702.      1550848.44      6814795.75
      1551258.21      6814875.62
#Sta/Elev= 30
  4412.2  1879.7  4472.9 1879.71  4523.9 1878.74  4641.6 1877.11  4715.9 1875.86
  4746.3 1874.69  4794.3 1876.06  4817.2 1874.48  4861.2 1875.04  4936.4 1874.34
    4959 1872.92    4983 1870.16  4983.3 1869.66  4986.8 1869.66    4987 1870.16
  4998.7  1871.6  5009.7 1872.06  5019.9 1874.25  5030.1 1875.66    5081 1876.13
  5094.7 1877.84  5101.4 1877.44  5121.8 1874.62  5126.6 1874.53  5152.3 1874.53
  5172.7 1875.73  5249.6  1877.2  5359.2  1878.2  5409.5 1878.97  5420.5 1879.64
#Mann= 8 ,-1 , 0
  4412.2     .07       0  4523.9    .035       0  4641.6     .07       0
  4936.4    .035       0    4983    .035       0    4987    .035       0
  5126.6     .07       0  5359.2    .035       0
Bank Sta=4983,4987
XS Rating Curve= 0 ,0
Exp/Cntr=0.3,0.1

Type RM Length L Ch R = 1 ,16028   ,236,236,236
BEGIN DESCRIPTION:
Elm 01 31 16028.3
END DESCRIPTION:
XS GIS Cut Line= 3
      1550292.91      6814879.09      1550817.19      6814986.72
      1551247.76      6815049.22
#Sta/Elev= 30
  4480.4 1878.26  4524.9  1877.8  4663.4 1875.41  4737.7 1874.69  4758.2 1873.48
  4778.6 1874.82  4819.4 1873.47  4846.4  1874.2  4931.7  1874.3  4941.9 1873.97
    4955 1872.54  4990.4 1869.29  4990.7 1868.79  4994.3 1868.79  4994.6 1869.29
  5011.9  1872.6  5023.5 1873.53  5033.6 1874.02    5074 1873.86  5094.2 1876.66
  5114.5 1873.67  5128.2 1873.69  5144.8 1873.65  5194.4 1875.24  5235.7 1874.99
  5255.9  1875.8  5296.3 1875.72  5316.5 1876.73  5369.2 1877.62  5450.7 1878.29
#Mann= 8 ,-1 , 0
  4480.4     .07       0  4524.9    .035       0  4663.4     .07       0
    4955    .035       0  4990.4    .035       0  4994.6    .035       0
  5128.2     .07       0  5369.2    .035       0
Bank Sta=4990.4,4994.6
XS Rating Curve= 0 ,0
Exp/Cntr=0.3,0.1

Type RM Length L Ch R = 1 ,15792   ,200,200,200
BEGIN DESCRIPTION:
Elm 01 31 15791.88
END DESCRIPTION:
XS GIS Cut Line= 3
      1550049.78      6815045.74      1550699.13      6815188.11
      1551150.25      6815264.45
#Sta/Elev= 30
  4324.7 1877.05    4330 1876.46  4391.5 1876.27  4449.9    1877  4568.6  1875.7
  4732.7 1874.48    4760 1874.29  4790.7 1872.75    4826 1873.87  4852.2 1872.81
  4882.9 1874.11  4967.7 1873.54  4989.5 1872.04  5012.6 1868.36  5012.9 1867.86
  5016.8 1868.36  5019.8 1868.53    5036 1868.95  5046.1 1870.79  5075.1 1873.56
  5117.1 1873.63  5127.3 1874.36  5135.5 1875.98  5157.7 1872.44  5179.3 1872.36
  5218.6 1874.12  5261.3 1873.28  5316.7 1875.39  5423.8 1875.76    5447  1876.1
#Mann= 8 ,-1 , 0
  4324.7     .07       0  4568.6    .035       0  4732.7     .07       0
  5012.6     .07       0  5016.8     .07       0  5019.8    .035       0
  5179.3     .07       0  5423.8    .035       0
Bank Sta=5012.6,5016.8
XS Rating Curve= 0 ,0
Exp/Cntr=0.3,0.1

Type RM Length L Ch R = 1 ,15592   ,322,322,322
BEGIN DESCRIPTION:
Elm 01 31 15591.55
END DESCRIPTION:
XS GIS Cut Line= 3
      1550074.09      6815247.13      1550660.94      6815375.61
      1551139.47      6815483.11
#Sta/Elev= 30
  4392.5 1875.35  4403.7 1875.85  4413.9 1877.43  4424.6 1875.44    4506 1874.56
  4567.3  1874.9  4754.1 1872.93  4782.4 1871.94  4823.4 1873.71  4854.1 1871.83
  4883.6 1873.09  4956.5 1872.86  4981.5 1871.59  4992.8 1869.25  5007.7 1868.54
  5015.8 1866.35  5016.1 1865.85    5020 1866.35    5025  1868.3  5037.1 1869.42
  5068.3 1872.54  5110.1 1873.81  5121.9  1875.5  5130.6 1875.54  5151.1 1871.84
  5184.7 1871.78  5208.5 1873.09  5243.4 1871.11  5284.4 1873.48  5483.7 1874.86
#Mann= 7 ,-1 , 0
  4392.5     .07       0  4567.3    .035       0  4754.1     .07       0
  5015.8     .07       0    5020     .07       0  5037.1    .035       0
  5184.7     .07       0
Bank Sta=5015.8,5020
XS Rating Curve= 0 ,0
Exp/Cntr=0.3,0.1

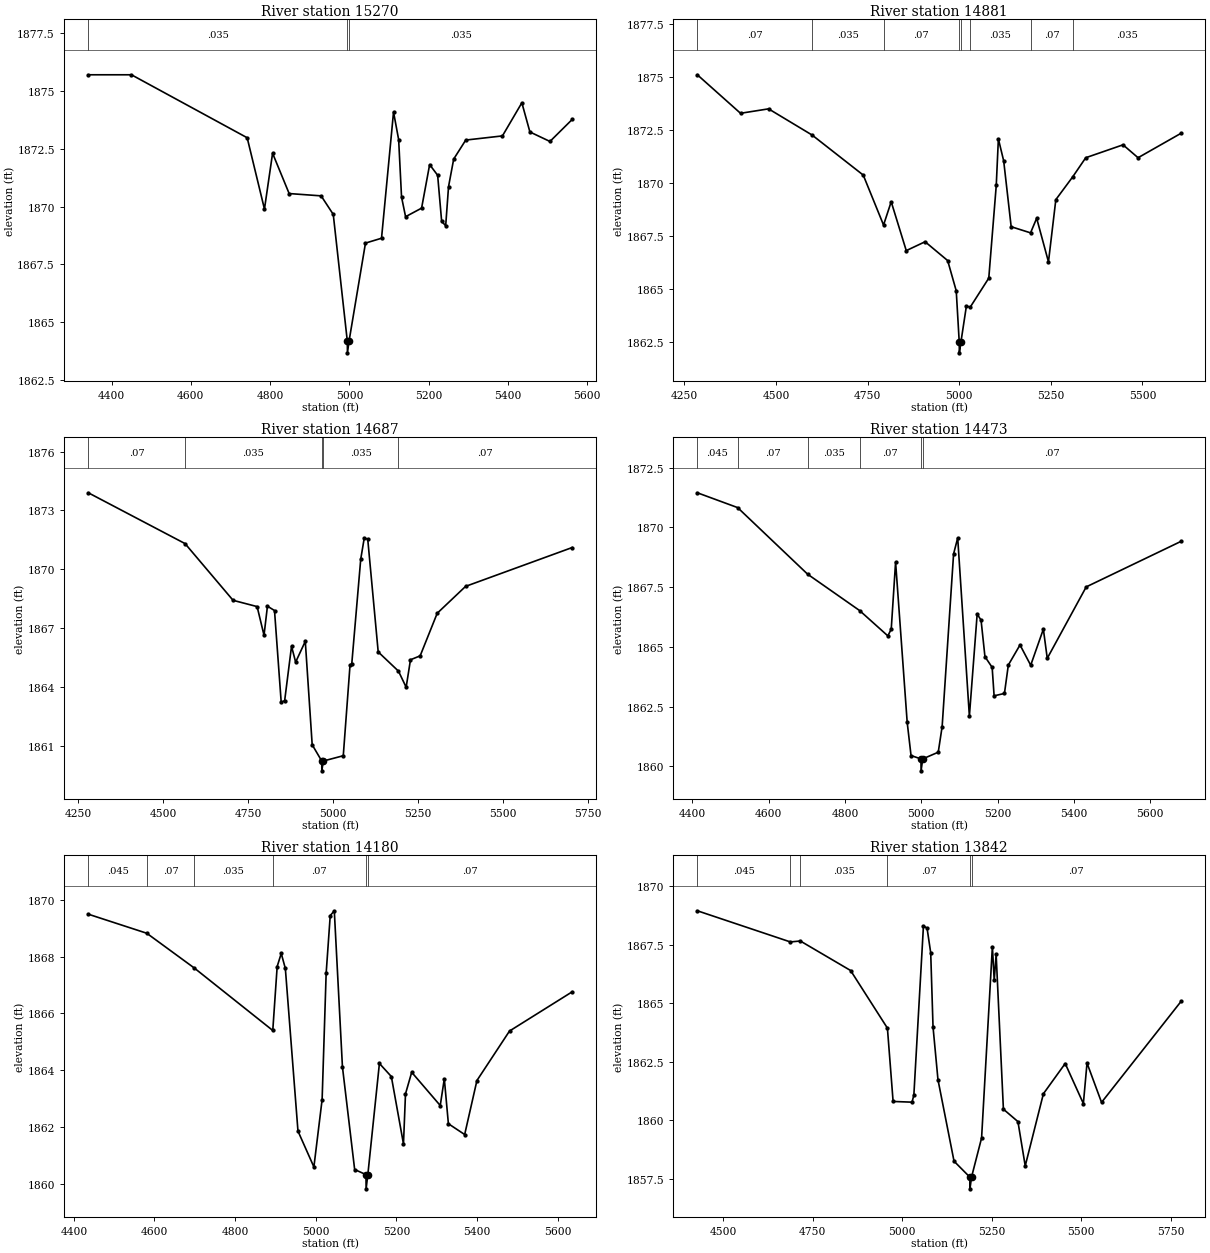
Type RM Length L Ch R = 1 ,15270   ,389,389,389
BEGIN DESCRIPTION:
Elm 01 31 15270.44
END DESCRIPTION:
XS GIS Cut Line= 3
      1549959.56      6815531.86      1550601.91       6815663.8
      1551160.45      6815750.53
#Sta/Elev= 30
  4341.2 1875.69  4450.1 1875.69  4742.1 1872.97  4785.7 1869.89  4806.2  1872.3
    4848 1870.56  4928.7 1870.46  4959.3 1869.66  4994.8 1864.18  4995.1 1863.68
  4999.1 1864.18  5040.6 1868.42  5081.1 1868.63  5111.4 1874.08  5124.3 1872.89
  5131.6 1870.41  5141.8 1869.56  5182.2 1869.93  5202.5 1871.81  5222.7 1871.35
  5232.8 1869.36    5243 1869.17  5250.2 1870.86  5263.2 1872.05  5293.6 1872.87
  5386.2 1873.05  5435.2 1874.48  5455.5 1873.22  5506.1 1872.81  5562.2 1873.76
#Mann= 3 ,-1 , 0
  4341.2    .035       0  4994.8    .035       0  4999.1    .035       0
Bank Sta=4994.8,4999.1
XS Rating Curve= 0 ,0
Exp/Cntr=0.3,0.1

Type RM Length L Ch R = 1 ,14881   ,194,194,194
BEGIN DESCRIPTION:
Elm 01 31 14880.64
END DESCRIPTION:
XS GIS Cut Line= 3
      1549810.25      6815858.25      1550497.75      6816021.44
      1551100.99      6816135.85
#Sta/Elev= 30
  4285.2 1875.12  4403.1  1873.3  4479.6 1873.51  4598.6 1872.27    4738 1870.38
  4793.4 1868.02  4814.3 1869.12  4855.4 1866.81  4906.8 1867.23  4968.4 1866.34
  4991.8 1864.91    5000 1862.48  5000.3 1861.98  5004.5 1862.48  5019.5 1864.19
    5030 1864.14  5080.6 1865.51    5101 1869.89  5106.8 1872.09  5121.3 1871.05
  5141.7 1867.94  5194.6 1867.65  5211.3 1868.34  5243.5 1866.28  5263.6 1869.22
  5309.8  1870.3  5345.2  1871.2    5447 1871.81    5488  1871.2  5605.8 1872.36
#Mann= 8 ,-1 , 0
  4285.2     .07       0  4598.6    .035       0  4793.4     .07       0
    5000     .07       0  5004.5     .07       0    5030    .035       0
  5194.6     .07       0  5309.8    .035       0
Bank Sta=5000,5004.5
XS Rating Curve= 0 ,0
Exp/Cntr=0.3,0.1

Type RM Length L Ch R = 1 ,14687   ,214,214,214
BEGIN DESCRIPTION:
Elm 01 31 14687.32
END DESCRIPTION:
XS GIS Cut Line= 3
      1549744.25      6816087.41      1550463.02        6816202.
      1551140.08      6816365.19
#Sta/Elev= 30
  4279.9  1873.9  4564.7 1871.31    4706 1868.42  4776.8  1868.1  4797.1 1866.64
  4807.2 1868.12    4828  1867.9  4847.7 1863.22  4857.9 1863.31  4878.1 1866.08
  4890.2 1865.27  4918.6 1866.33  4938.9 1861.06    4967 1860.23  4967.3 1859.73
  4971.5 1860.23  5030.4  1860.5  5050.2  1865.1  5055.4 1865.18  5081.8 1870.52
  5092.1 1871.59  5102.4 1871.54  5133.2 1865.79  5192.9 1864.81  5215.5 1863.99
  5228.2 1865.39  5256.7 1865.59  5306.9 1867.76  5390.4 1869.13  5704.2 1871.11
#Mann= 5 ,-1 , 0
  4279.9     .07       0  4564.7    .035       0    4967    .035       0
  4971.5    .035       0  5192.9     .07       0
Bank Sta=4967,4971.5
XS Rating Curve= 0 ,0
Exp/Cntr=0.3,0.1

Type RM Length L Ch R = 1 ,14473   ,293,293,293
BEGIN DESCRIPTION:
Elm 01 31 14473.37
END DESCRIPTION:
XS GIS Cut Line= 3
      1549782.49      6816288.81       1550365.8      6816386.03
      1551028.96      6816521.44
#Sta/Elev= 30
    4413 1871.45  4518.6 1870.83  4702.2 1868.04  4838.3 1866.52  4912.3 1865.46
  4921.2 1865.74  4932.6 1868.55    4963 1861.84  4973.1 1860.45  4999.1 1860.31
  4999.4 1859.81  5003.7 1860.31  5044.4 1860.59  5054.6 1861.66  5084.6 1868.89
  5095.4 1869.56    5126  1862.1  5146.4 1866.37  5156.6 1866.12  5166.8 1864.59
  5185.7 1864.14  5190.8 1862.95  5217.9 1863.05  5228.1 1864.24  5258.7 1865.08
  5286.7 1864.23  5319.9 1865.74  5330.1 1864.52  5432.2 1867.51  5681.2 1869.42
#Mann= 6 ,-1 , 0
    4413    .045       0  4518.6     .07       0  4702.2    .035       0
  4838.3     .07       0  4999.1     .07       0  5003.7     .07       0
Bank Sta=4999.1,5003.7
XS Rating Curve= 0 ,0
Exp/Cntr=0.3,0.1

Type RM Length L Ch R = 1 ,14180   ,338,338,338
BEGIN DESCRIPTION:
Elm 01 31 14180.36
END DESCRIPTION:
XS GIS Cut Line= 3
      1549692.19      6816552.69      1550265.11      6816642.97
      1550878.84      6816733.12
#Sta/Elev= 30
  4435.9 1869.49  4580.9 1868.82  4698.5  1867.6  4893.5  1865.4  4904.4 1867.65
  4914.5 1868.11  4924.7 1867.58    4956 1861.86  4995.5  1860.6  5015.9 1862.97
  5025.9 1867.41    5036 1869.44  5046.1 1869.61  5066.3 1864.12  5096.6 1860.51
  5124.7 1860.33    5125 1859.83  5129.3 1860.33    5158 1864.24  5187.6 1863.78
  5217.7 1861.41  5222.7 1863.17  5238.1 1863.93  5308.9 1862.76    5319  1863.7
  5329.1 1862.12  5369.5 1861.74  5399.9 1863.64  5480.7 1865.38  5636.2 1866.76
#Mann= 6 ,-1 , 0
  4435.9    .045       0  4580.9     .07       0  4698.5    .035       0
  4893.5     .07       0  5124.7     .07       0  5129.3     .07       0
Bank Sta=5124.7,5129.3
XS Rating Curve= 0 ,0
Exp/Cntr=0.3,0.1

Type RM Length L Ch R = 1 ,13842   ,513,513,513
BEGIN DESCRIPTION:
Elm 01 31 13841.82
END DESCRIPTION:
XS GIS Cut Line= 3
      1549494.31      6816799.23       1550053.3      6816906.86
      1550824.13      6817045.75
#Sta/Elev= 30
  4427.1 1868.94  4687.1 1867.61    4715 1867.65  4855.5 1866.39  4958.4 1863.93
  4974.3  1860.8  5027.2 1860.77  5032.3 1861.07  5059.1 1868.29  5069.2  1868.2
  5079.4 1867.15  5085.9 1863.98  5099.7 1861.73  5144.6 1858.25  5188.8 1857.57
  5189.1 1857.07  5193.5 1857.57  5221.6 1859.24  5251.8 1867.41  5256.9 1865.97
  5262.3 1867.08  5282.6 1860.47  5323.2 1859.94  5343.6 1858.05  5394.4 1861.13
  5455.3 1862.42  5506.1 1860.71  5516.3 1862.44  5556.9 1860.76  5779.6 1865.08
#Mann= 6 ,-1 , 0
  4427.1    .045       0  4687.1     .07       0    4715    .035       0
  4958.4     .07       0  5188.8     .07       0  5193.5     .07       0
Bank Sta=5188.8,5193.5
XS Rating Curve= 0 ,0
Exp/Cntr=0.3,0.1

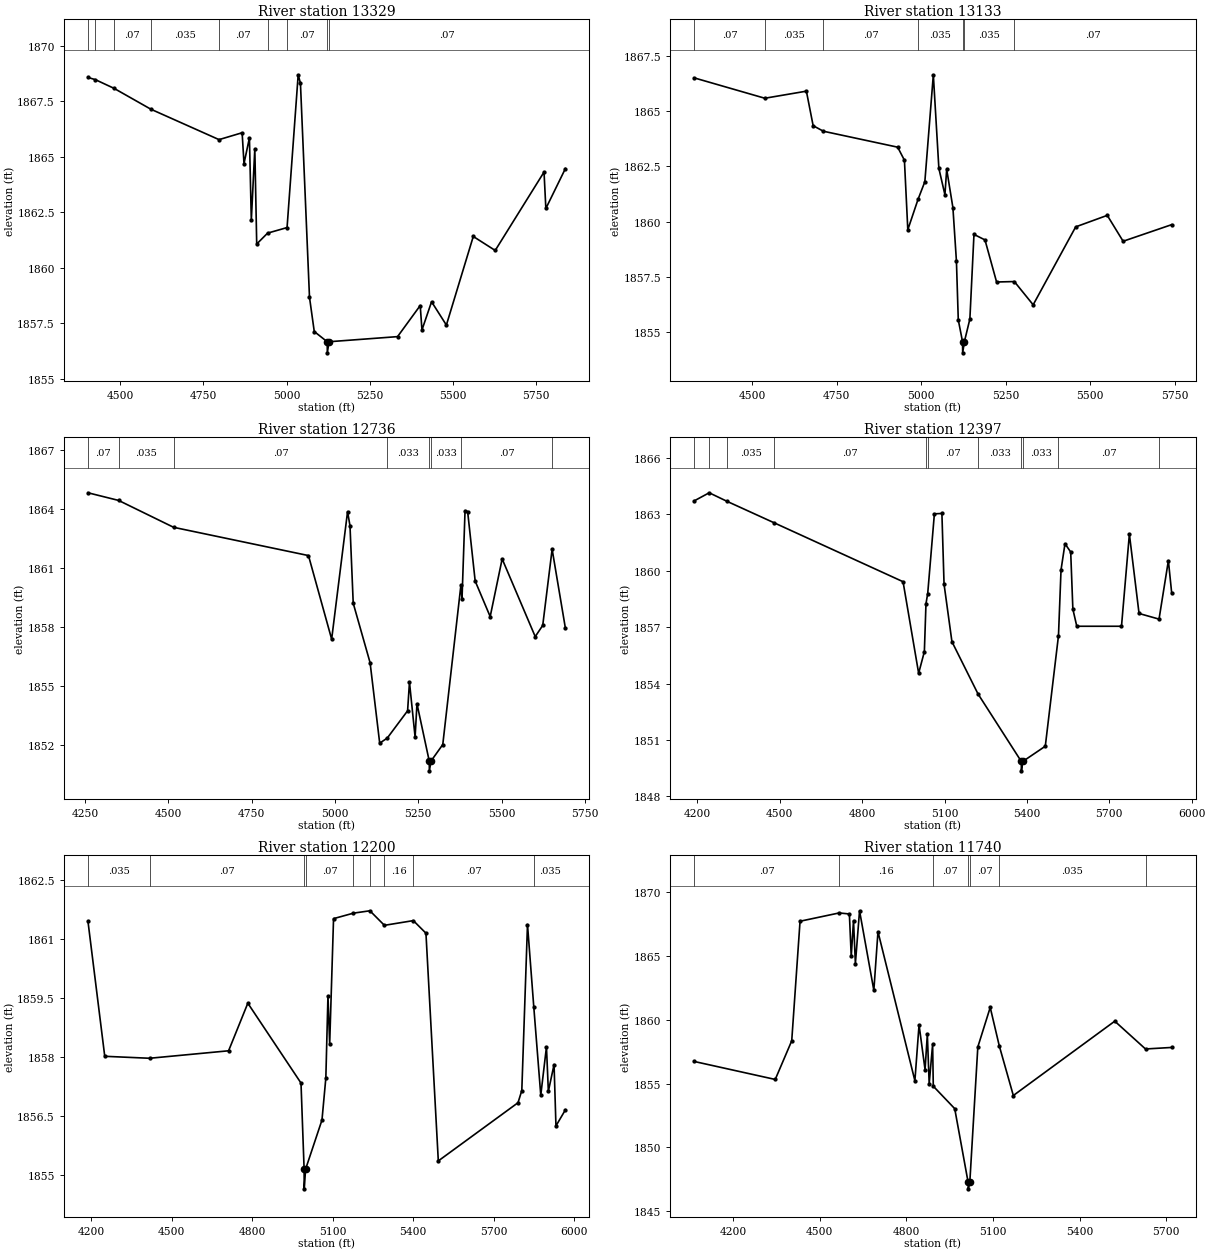
Type RM Length L Ch R = 1 ,13329   ,196,196,196
BEGIN DESCRIPTION:
Elm 01 31 13467.89
END DESCRIPTION:
XS GIS Cut Line= 3
      1549473.41      6817142.95      1549935.61      6817391.43
       1550811.6      6817145.55
#Sta/Elev= 30
    4403 1868.57  4425.3 1868.47  4481.2 1868.08  4591.9 1867.14  4796.8 1865.77
  4866.2 1866.08  4871.8 1864.69  4888.1 1865.85  4893.8 1862.14  4904.3 1865.36
    4910 1861.07  4942.7 1861.56  5001.2 1861.81  5034.6 1868.69  5041.4 1868.31
  5068.6 1858.67  5082.9 1857.13  5121.8 1856.67  5122.2 1856.17  5127.2 1856.67
  5333.2  1856.9  5401.3  1858.3  5406.5  1857.2  5435.4 1858.47  5479.9 1857.42
  5560.7 1861.41  5626.6 1860.78  5773.3 1864.31  5778.8 1862.67  5837.6 1864.47
#Mann= 9 ,-1 , 0
    4403     .07       0  4425.3    .045       0  4481.2     .07       0
  4591.9    .035       0  4796.8     .07       0  4942.7    .035       0
  5001.2     .07       0  5121.8    .035       0  5127.2     .07       0
Bank Sta=5121.8,5127.2
XS Rating Curve= 0 ,0
Exp/Cntr=0.3,0.1

Type RM Length L Ch R = 1 ,13133   ,397,397,397
BEGIN DESCRIPTION:
Elm 01 31 13133.23
END DESCRIPTION:
XS GIS Cut Line= 3
       1549383.2      6817552.69       1550053.3      6817552.69
      1550768.62      6817354.77
#Sta/Elev= 30
  4328.5  1866.5  4537.4 1865.58  4660.3  1865.9  4680.3 1864.34  4710.6 1864.09
  4930.3 1863.37  4950.3 1862.78  4960.3 1859.64  4990.5 1861.01  5010.7 1861.81
  5035.8 1866.64  5052.2 1862.41  5070.1 1861.22  5075.3 1862.37  5093.7 1860.64
  5104.1 1858.23  5109.6 1855.57  5122.2 1854.58  5122.6 1854.08  5127.6 1854.58
  5143.9 1855.61    5156 1859.43  5188.6 1859.18  5222.9 1857.28  5275.4  1857.3
  5331.1 1856.25  5456.9 1859.77  5550.3 1860.29  5597.2 1859.12  5740.8 1859.87
#Mann= 7 ,-1 , 0
  4328.5     .07       0  4537.4    .035       0  4710.6     .07       0
  4990.5    .035       0  5122.2    .035       0  5127.6    .035       0
  5275.4     .07       0
Bank Sta=5122.2,5127.6
XS Rating Curve= 0 ,0
Exp/Cntr=0.3,0.1

Type RM Length L Ch R = 1 ,12736   ,339,339,339
BEGIN DESCRIPTION:
Elm 01 31 12735.71
END DESCRIPTION:
XS GIS Cut Line= 3
      1549414.39      6817941.58      1550150.52      6817920.75
       1550775.5       6817615.2
#Sta/Elev= 30
  4259.3 1864.83  4351.2 1864.44  4516.2 1863.07  4920.7 1861.63  4990.2 1857.37
  5037.9 1863.87  5045.2 1863.15  5054.9  1859.2  5105.5 1856.17  5134.3 1852.07
    5157 1852.33    5218 1853.72  5223.6 1855.18  5240.5 1852.38  5246.1 1854.08
  5282.9 1851.16  5283.3 1850.66  5288.3 1851.16  5323.5    1852  5377.9 1860.12
  5381.2 1859.42  5390.3 1863.92  5398.1 1863.87  5420.7 1860.33  5465.7 1858.52
  5501.6 1861.46  5600.8  1857.5  5623.3 1858.07  5651.5 1861.95  5691.4 1857.92
#Mann= 8 ,-1 , 0
  4259.3     .07       0  4351.2    .035       0  4516.2     .07       0
    5157    .033       0  5282.9     .07       0  5288.3    .033       0
  5377.9     .07       0  5651.5    .035       0
Bank Sta=5282.9,5288.3
XS Rating Curve= 0 ,0
Exp/Cntr=0.3,0.1

Type RM Length L Ch R = 1 ,12397   ,197,197,197
BEGIN DESCRIPTION:
Elm 01 31 12396.89
END DESCRIPTION:
XS GIS Cut Line= 3
      1549282.46      6818472.83      1550056.77       6818226.3
      1550771.05      6817636.85
#Sta/Elev= 30
  4188.5 1863.72  4243.1 1864.15  4307.2  1863.7    4480 1862.55    4949 1859.42
  5005.8 1854.55  5026.6  1855.7  5032.5 1858.25  5038.8 1858.79  5063.1 1863.03
  5090.5 1863.05  5098.3 1859.29    5127 1856.23    5222 1853.45  5379.6 1849.86
    5380 1849.36  5385.1 1849.86    5467 1850.67    5515 1856.55  5524.3 1860.05
  5538.7 1861.44  5559.5    1861  5567.4 1857.96  5581.7 1857.05  5744.5 1857.05
  5773.2 1861.95  5808.4 1857.73  5881.2 1857.43  5915.2 1860.54  5927.2 1858.83
#Mann= 11 ,-1 , 0
  4188.5    .035       0  4243.1     .07       0  4307.2    .035       0
    4480     .07       0  5032.5     .16       0  5038.8     .07       0
    5222    .033       0  5379.6     .07       0  5385.1    .033       0
    5515     .07       0  5881.2    .035       0
Bank Sta=5379.6,5385.1
XS Rating Curve= 0 ,0
Exp/Cntr=0.3,0.1

Type RM Length L Ch R = 1 ,12200   ,460,460,460
BEGIN DESCRIPTION:
Elm 01 31 12186.87
END DESCRIPTION:
XS GIS Cut Line= 3
      1549640.11      6819011.02      1550436.16      6818038.15
      1550808.98        6817672.
#Sta/Elev= 30
  4188.5 1861.45    4251 1858.02  4418.3 1857.97  4712.6 1858.16  4784.3 1859.37
  4982.5 1857.34  4994.1 1855.15  4994.5 1854.65  4999.6 1855.15  5060.7  1856.4
  5075.1 1857.47    5083 1859.56  5089.4 1858.34  5103.8 1861.52  5178.1 1861.66
  5239.3 1861.72  5293.4 1861.35  5401.2 1861.47  5448.2 1861.15  5494.3 1855.36
  5791.4 1856.84  5805.5 1857.15  5826.7 1861.37  5850.2 1859.27  5876.2 1857.03
  5897.4 1858.26  5904.5 1857.13  5925.7 1857.81  5932.8 1856.25  5968.1 1856.66
#Mann= 9 ,-1 , 0
  4188.5    .035       0  4418.3     .07       0  4994.1     .07       0
  4999.6     .07       0  5178.1     .16       0  5239.3     .07       0
  5293.4     .16       0  5401.2     .07       0  5850.2    .035       0
Bank Sta=4994.1,4999.6
XS Rating Curve= 0 ,0
Exp/Cntr=0.3,0.1

Type RM Length L Ch R = 1 ,11740   ,472,472,472
BEGIN DESCRIPTION:
Elm 01 31 11736.79
END DESCRIPTION:
XS GIS Cut Line= 3
      1549976.74      6818975.04      1550499.58      6818336.45
      1550920.41      6817623.74
#Sta/Elev= 30
  4065.7 1856.73  4346.2 1855.32  4403.3 1858.35  4432.1 1867.73  4567.5 1868.38
  4602.9  1868.3  4609.3 1864.98  4617.2 1867.78  4623.7 1864.41  4638.1 1868.55
  4687.6 1862.31  4701.9 1866.91  4829.7 1855.22  4844.1  1859.6  4864.9 1856.09
  4872.8 1858.86  4879.2 1854.98  4891.1 1858.08  4893.4 1854.79  4967.6 1853.03
  5014.1 1847.24  5014.6 1846.74  5019.8 1847.24  5047.6 1857.87  5090.5 1860.97
  5121.8 1857.96  5170.5 1854.06  5521.7 1859.89  5628.1 1857.71  5718.7 1857.83
#Mann= 7 ,-1 , 0
  4065.7     .07       0  4567.5     .16       0  4891.1     .07       0
  5014.1     .07       0  5019.8     .07       0  5121.8    .035       0
  5628.1     .07       0
Bank Sta=5014.1,5019.8
XS Rating Curve= 0 ,0
Exp/Cntr=0.3,0.1