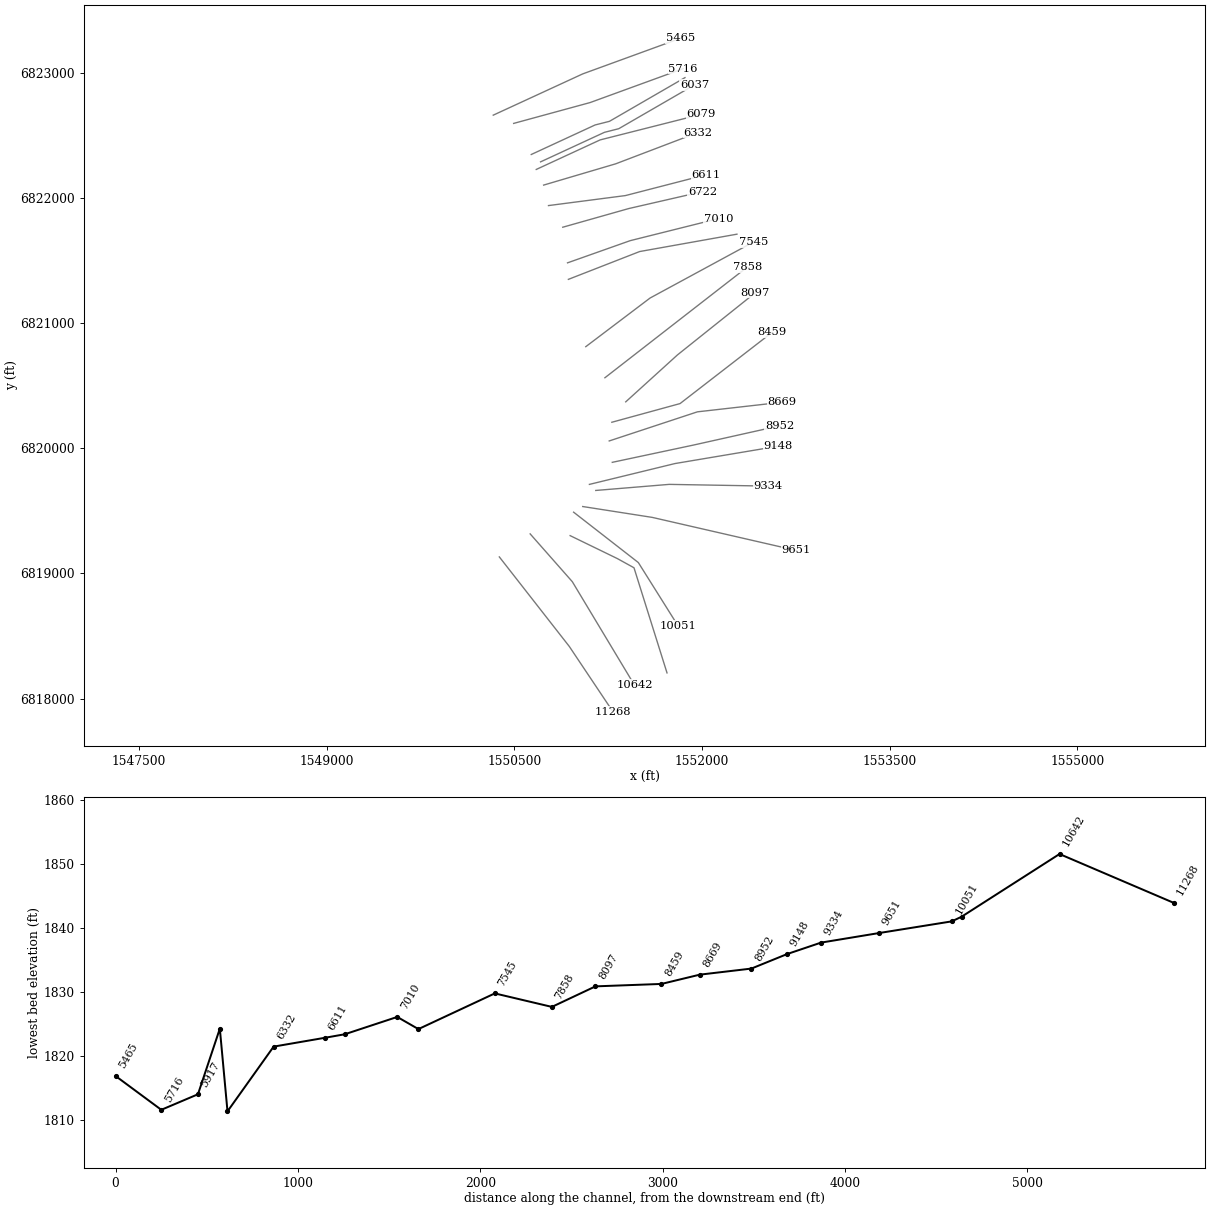
HEC-RAS study Elm 01 31.prj: Elm 01 31 Base Level Engineering

--- Elm 01 31.g01 (geometry) --- (continued)

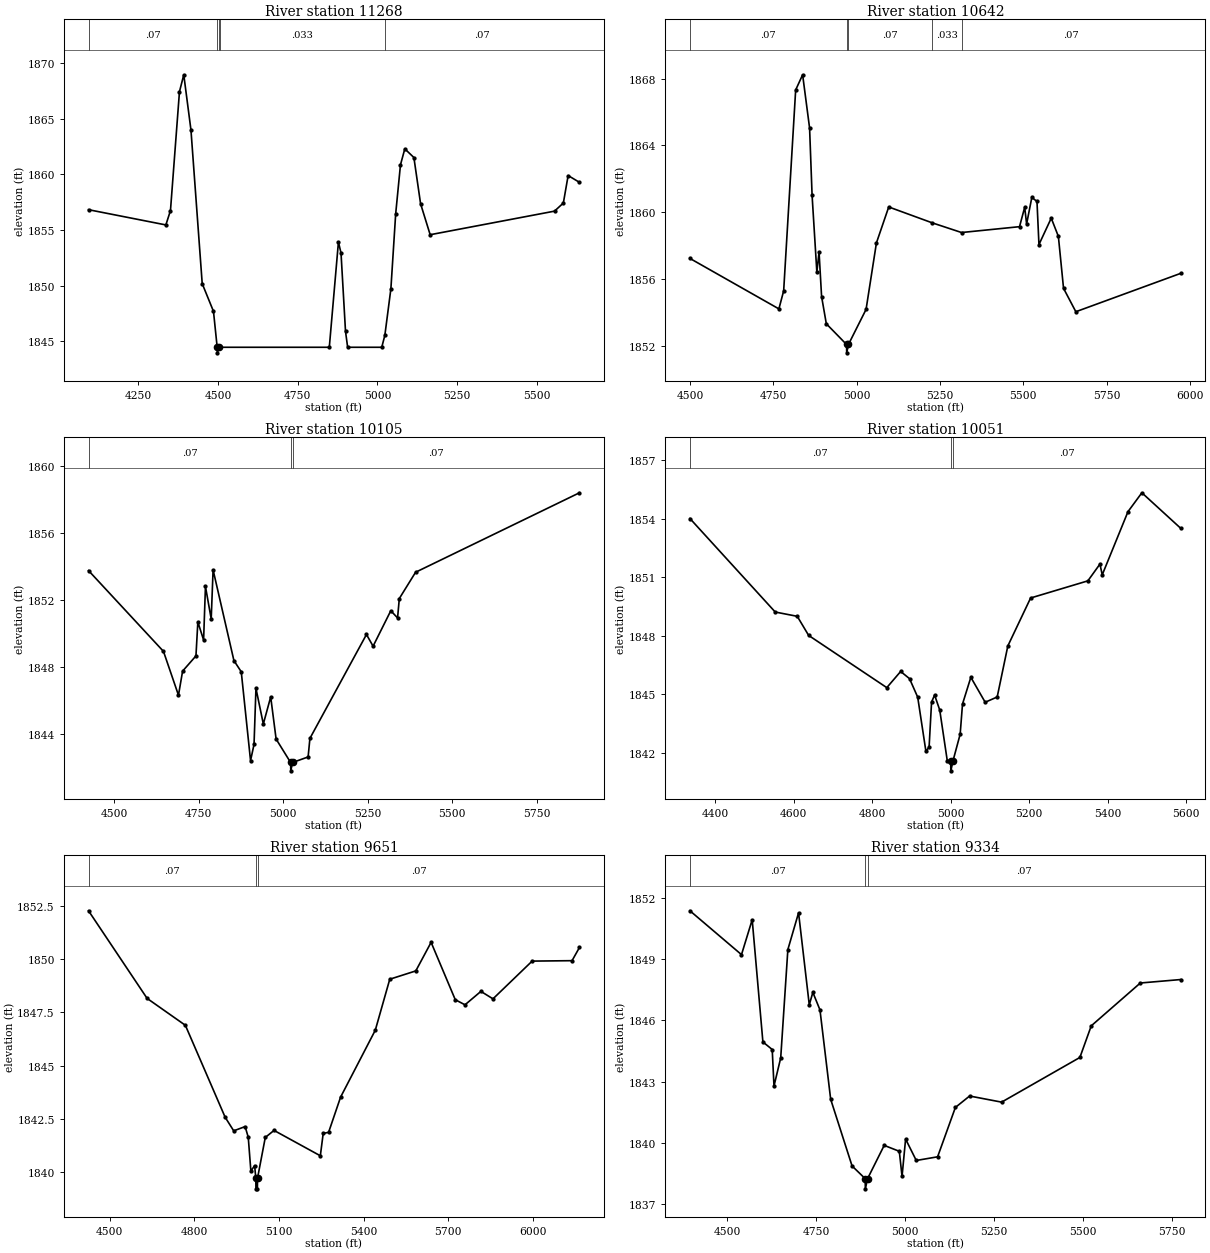
Type RM Length L Ch R = 1 ,11268   ,626,626,626
BEGIN DESCRIPTION:
Elm 01 31 11268.35
END DESCRIPTION:
XS GIS Cut Line= 3
      1550379.67      6819132.59      1550938.72      6818417.28
      1551289.39        6817893.
#Sta/Elev= 30
  4094.5 1856.83  4336.9 1855.46  4351.3 1856.75  4379.5 1867.44    4393 1868.96
  4415.5    1864  4450.8 1850.18  4486.1 1847.69  4497.7 1844.46  4498.2 1843.96
  4503.4 1844.46  4506.1 1844.46  4849.1 1844.46  4877.7 1853.92  4885.8 1852.94
  4899.9 1845.88  4906.6 1844.46  5013.5 1844.46  5023.2 1845.54  5042.1 1849.72
  5057.1 1856.45  5072.1 1860.86  5085.7  1862.3  5114.2 1861.52  5135.2 1857.36
  5165.2 1854.58  5554.9  1856.7  5582.6 1857.43  5597.6  1859.9  5633.1 1859.29
#Mann= 5 ,-1 , 0
  4094.5     .07       0  4497.7    .033       0  4503.4     .07       0
  4506.1    .033       0  5023.2     .07       0
Bank Sta=4497.7,4503.4
XS Rating Curve= 0 ,0
Exp/Cntr=0.3,0.1

Type RM Length L Ch R = 1 ,10642   ,537,537,537
BEGIN DESCRIPTION:
Elm 01 31 10642.03
END DESCRIPTION:
XS GIS Cut Line= 3
      1550626.25      6819316.55      1550963.02      6818934.64
      1551459.56      6818108.23
#Sta/Elev= 30
  4499.4 1857.24  4766.4 1854.22  4780.7  1855.3  4816.7 1867.32  4837.6 1868.23
  4858.5 1865.04    4866 1861.01  4880.3 1856.42  4886.9 1857.62  4894.5 1854.96
  4908.7 1853.33  4969.4 1852.09  4969.9 1851.59  4975.1 1852.09    5028 1854.19
  5059.1 1858.17    5096 1860.32  5226.4 1859.37  5314.5 1858.79  5488.5 1859.14
    5504  1860.3  5509.8  1859.3  5525.4 1860.89  5540.9 1860.65  5546.8 1858.07
  5583.7 1859.65  5605.1 1858.56  5620.6 1855.45  5657.5 1854.05  5972.7 1856.35
#Mann= 5 ,-1 , 0
  4499.4     .07       0  4969.4     .07       0  4975.1     .07       0
  5226.4    .033       0  5314.5     .07       0
Bank Sta=4969.4,4975.1
XS Rating Curve= 0 ,0
Exp/Cntr=0.3,0.1

Type RM Length L Ch R = 1 ,10105   ,54,54,54
BEGIN DESCRIPTION:
Elm 01 31 10105.04
END DESCRIPTION:
XS GIS Cut Line= 4
      1550945.66       6819302.7      1551324.13      6819118.67
      1551456.08      6819045.75      1551719.96      6818205.51
#Sta/Elev= 30
  4423.7 1853.76  4645.4 1848.93  4689.8 1846.31    4702 1847.75  4741.5 1848.66
  4747.1 1850.69  4764.1 1849.61  4769.6 1852.81  4786.6 1850.87  4792.2  1853.8
  4853.8 1848.38  4875.5 1847.71    4903  1842.4  4913.3 1843.37    4919 1846.72
  4940.8 1844.59  4962.6 1846.21  4978.6 1843.69  5021.5 1842.29    5022 1841.79
  5027.3 1842.29  5073.3 1842.62  5078.6 1843.73  5245.9 1849.94  5265.5 1849.24
  5317.9 1851.36  5337.9 1850.93  5343.1 1852.09  5391.2 1853.66    5876 1858.41
#Mann= 3 ,-1 , 0
  4423.7     .07       0  5021.5     .07       0  5027.3     .07       0
Bank Sta=5021.5,5027.3
XS Rating Curve= 0 ,0
Exp/Cntr=0.3,0.1

Type RM Length L Ch R = 1 ,10051   ,400,400,400
BEGIN DESCRIPTION:
Elm 01 31 10050.72
END DESCRIPTION:
XS GIS Cut Line= 3
      1550973.43       6819490.2       1551490.8      6819087.42
      1551806.78      6818583.93
#Sta/Elev= 30
  4335.9 1854.01  4553.1 1849.21  4609.2 1848.99  4638.2 1848.01  4837.2 1845.33
  4872.5 1846.16  4895.1 1845.79  4915.9 1844.84  4936.8 1842.06  4944.9 1842.28
  4951.2 1844.59  4958.9 1844.95    4972 1844.18  4991.1 1841.59  4999.8 1841.56
  5000.3 1841.06  5005.6 1841.56    5024 1842.94    5030 1844.49  5051.2 1845.86
  5087.7 1844.58  5118.3 1844.85  5145.4 1847.47  5203.4 1849.93  5349.2 1850.81
  5379.9 1851.67  5385.8 1851.12  5451.3 1854.36  5486.7 1855.33    5586  1853.5
#Mann= 3 ,-1 , 0
  4335.9     .07       0  4999.8     .07       0  5005.6     .07       0
Bank Sta=4999.8,5005.6
XS Rating Curve= 0 ,0
Exp/Cntr=0.3,0.1

Type RM Length L Ch R = 1 ,9651    ,317,317,317
BEGIN DESCRIPTION:
Elm 01 31 9650.51
END DESCRIPTION:
XS GIS Cut Line= 3
      1551046.37      6819535.33      1551601.91      6819448.53
      1552750.64      6819184.77
#Sta/Elev= 30
  4424.3 1852.27  4632.1 1848.16  4767.7  1846.9  4908.7 1842.59  4939.1 1841.95
  4979.6 1842.15  4990.7 1841.65    5000 1840.06  5013.3 1840.32  5017.5 1839.73
    5018 1839.23  5023.1 1839.23  5023.6 1839.73  5051.1 1841.64  5082.1 1841.97
  5246.3 1840.78  5256.5 1841.83  5275.6 1841.88  5318.1 1843.53  5441.2 1846.67
  5492.5 1849.06  5584.8 1849.45  5639.1 1850.79  5724.8  1848.1  5759.3 1847.86
  5815.7 1848.49  5858.5 1848.14  5997.4 1849.91  6138.9 1849.93  6165.2 1850.55
#Mann= 3 ,-1 , 0
  4424.3     .07       0  5017.5     .07       0  5023.6     .07       0
Bank Sta=5017.5,5023.6
XS Rating Curve= 0 ,0
Exp/Cntr=0.3,0.1

Type RM Length L Ch R = 1 ,9334    ,186,186,186
BEGIN DESCRIPTION:
Elm 01 31 9334.1
END DESCRIPTION:
XS GIS Cut Line= 3
      1551150.53       6819663.8      1551737.33      6819712.42
        1552529.      6819698.53
#Sta/Elev= 30
  4394.9 1851.37  4539.9 1849.22    4570 1850.93  4600.1 1844.94  4626.3 1844.57
  4631.3 1842.78  4650.2 1844.16  4670.3 1849.47  4700.4 1851.27  4730.5 1846.76
  4740.6 1847.37  4760.6 1846.51  4790.7 1842.13  4850.9 1838.86  4887.7 1838.24
  4888.2 1837.74  4894.5 1838.24  4941.2 1839.87  4983.7 1839.58  4991.4 1838.35
  5001.4 1840.18  5031.4 1839.13  5091.4 1839.31  5141.4 1841.73  5181.4 1842.29
  5271.4 1841.99  5491.5 1844.18  5523.5 1845.73  5661.5 1847.83  5775.5    1848
#Mann= 3 ,-1 , 0
  4394.9     .07       0  4887.7     .07       0  4894.5     .07       0
Bank Sta=4887.7,4894.5
XS Rating Curve= 0 ,0
Exp/Cntr=0.3,0.1

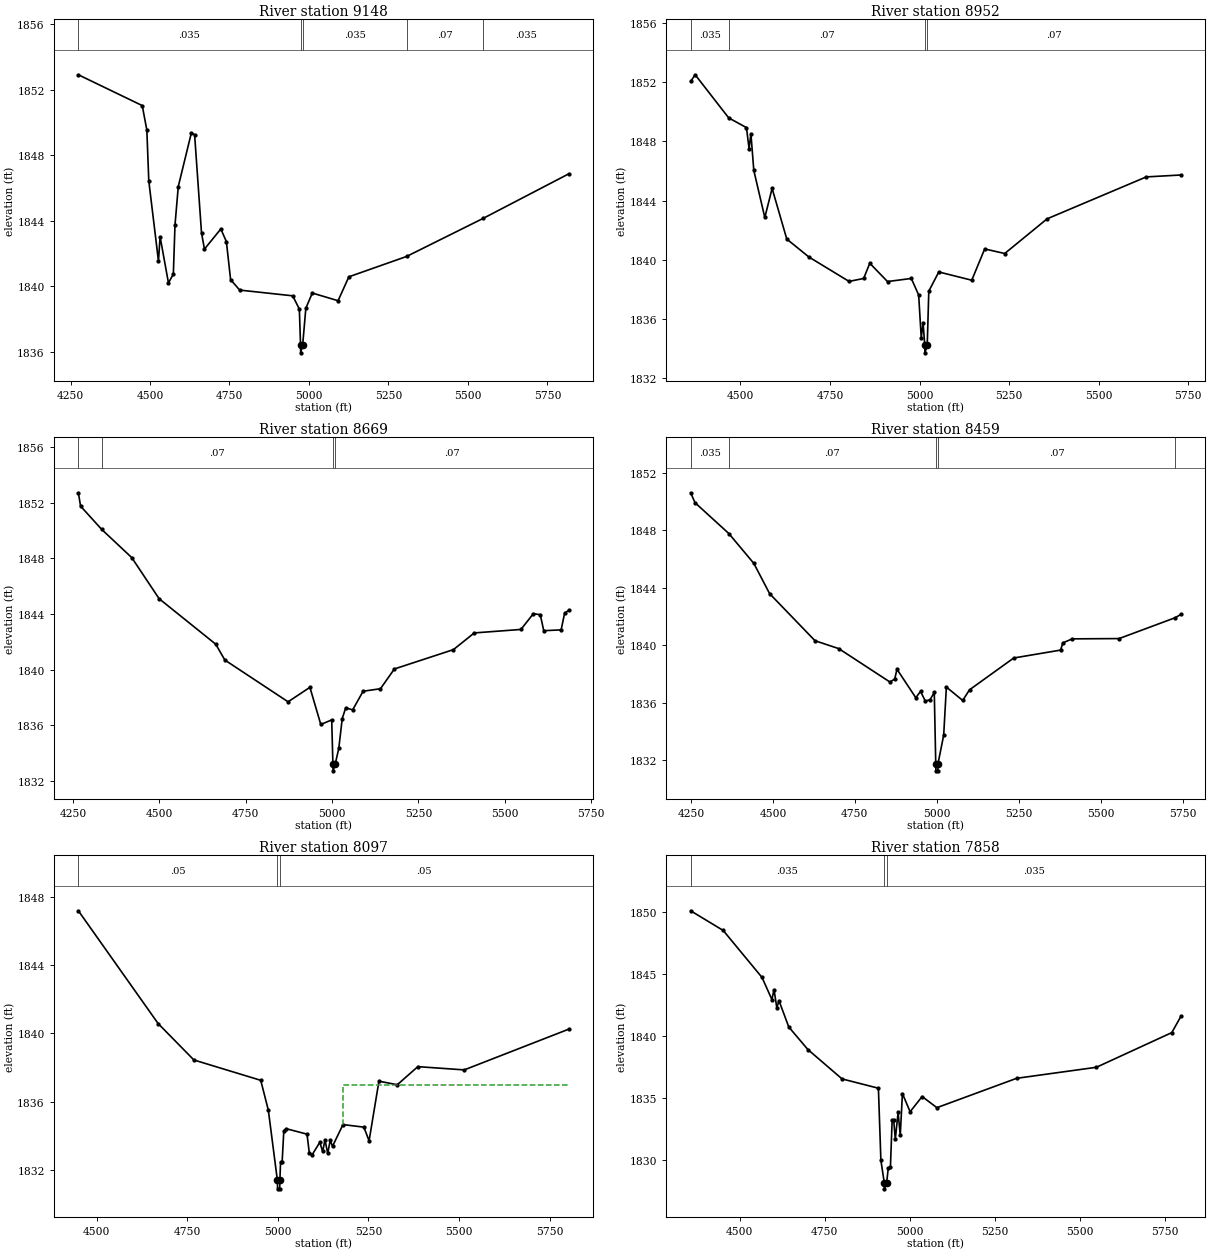
Type RM Length L Ch R = 1 ,9148    ,196,196,196
BEGIN DESCRIPTION:
Elm 01 31 9178.38
END DESCRIPTION:
XS GIS Cut Line= 3
      1551099.78      6819712.28      1551783.76      6819878.94
      1552610.08      6820017.81
#Sta/Elev= 30
  4274.7 1852.92  4475.6 1851.04    4490 1849.55  4496.2 1846.44  4526.6 1841.55
  4531.7 1843.04    4558 1840.22  4573.4 1840.75  4578.6 1843.75  4588.9  1846.1
    4630 1849.37  4640.3 1849.26    4662 1843.27  4671.2 1842.28  4722.7 1843.51
  4740.2 1842.74  4753.5 1840.42    4782 1839.78  4948.8 1839.43  4969.7 1838.62
  4973.4 1836.45  4973.9 1835.95  4980.2 1836.45  4990.1 1838.67  5010.4  1839.6
  5091.5 1839.13  5125.4 1840.59  5306.7 1841.83  5548.2 1844.16  5816.6 1846.87
#Mann= 5 ,-1 , 0
  4274.7    .035       0  4973.4    .035       0  4980.2    .035       0
  5306.7     .07       0  5548.2    .035       0
Bank Sta=4973.4,4980.2
XS Rating Curve= 0 ,0
Exp/Cntr=0.3,0.1

Type RM Length L Ch R = 1 ,8952    ,283,283,283
BEGIN DESCRIPTION:
Elm 01 31 8866.75
END DESCRIPTION:
XS GIS Cut Line= 3
      1551282.56      6819888.62      1551935.38      6820027.52
       1552619.4       6820180.3
#Sta/Elev= 30
  4361.1 1852.07  4373.8 1852.52  4467.3  1849.6  4516.9 1848.94  4524.2 1847.51
  4529.3 1848.53  4537.4 1846.04  4568.1 1842.85  4588.5 1844.82  4629.4 1841.39
  4690.8 1840.18  4803.2 1838.52  4844.1 1838.72    4861 1839.75  4910.6 1838.51
    4977 1838.72  4997.5  1837.6  5004.7  1834.7  5009.8 1835.73  5014.5 1834.18
    5015 1833.68  5021.4 1834.18  5025.8 1837.86  5053.7 1839.16  5145.7  1838.6
  5181.8 1840.72  5237.7 1840.41    5356 1842.76  5632.7  1845.6  5729.4 1845.73
#Mann= 4 ,-1 , 0
  4361.1    .035       0  4467.3     .07       0  5014.5     .07       0
  5021.4     .07       0
Bank Sta=5014.5,5021.4
XS Rating Curve= 0 ,0
Exp/Cntr=0.3,0.1

Type RM Length L Ch R = 1 ,8669    ,210,210,210
BEGIN DESCRIPTION:
Elm 01 31 8669.19
END DESCRIPTION:
XS GIS Cut Line= 3
      1551258.12      6820059.62      1551963.02      6820292.28
       1552636.6      6820368.66
#Sta/Elev= 30
    4265 1852.71  4271.4 1851.75  4332.5 1850.08  4419.7 1848.05  4498.9  1845.1
  4662.9 1841.83  4689.4 1840.69  4872.5 1837.69  4935.7 1838.73  4967.3 1836.06
  4998.9 1836.39  5002.3 1833.23  5002.8 1832.73  5009.2 1833.23  5019.4 1834.35
  5029.4 1836.49  5039.5 1837.26  5059.6 1837.11  5089.8 1838.45  5140.1 1838.63
  5180.4 1840.05  5351.5 1841.44  5411.9 1842.64    5547 1842.89    5583 1844.02
  5603.1 1843.95  5613.1  1842.8  5663.5 1842.86  5673.5 1844.05  5685.2 1844.26
#Mann= 4 ,-1 , 0
    4265    .035       0  4332.5     .07       0  5002.3     .07       0
  5009.2     .07       0
Bank Sta=5002.3,5009.2
XS Rating Curve= 0 ,0
Exp/Cntr=0.3,0.1

Type RM Length L Ch R = 1 ,8459    ,362,362,362
BEGIN DESCRIPTION:
Elm 01 31 8459.37
END DESCRIPTION:
XS GIS Cut Line= 3
      1551278.98      6820208.94      1551824.13      6820358.25
      1552560.09      6820927.57
#Sta/Elev= 30
    4249  1850.6  4262.4 1849.91  4365.5 1847.77  4441.9 1845.69    4490 1843.59
  4628.5 1840.32  4701.1 1839.77  4857.1 1837.45  4871.6 1837.66  4878.5 1838.34
  4935.9 1836.36  4950.4  1836.8  4964.9 1836.13  4979.4 1836.22  4992.3 1836.73
  4996.8 1831.78  4997.3 1831.28  5003.2 1831.28  5003.7 1831.78    5021 1833.76
  5029.2  1837.1    5079 1836.17  5099.8 1836.91  5234.7 1839.12  5377.8 1839.67
  5384.3 1840.17  5413.1 1840.45  5556.2 1840.47  5727.4 1841.92  5744.7 1842.15
#Mann= 5 ,-1 , 0
    4249    .035       0  4365.5     .07       0  4996.8     .07       0
  5003.7     .07       0  5727.4    .035       0
Bank Sta=4996.8,5003.7
XS Rating Curve= 0 ,0
Exp/Cntr=0.3,0.1

Type RM Length L Ch R = 1 ,8097    ,239,239,239
BEGIN DESCRIPTION:
Elm 01 31 8097.46
END DESCRIPTION:
XS GIS Cut Line= 3
      1551390.12      6820372.15       1551803.3      6820747.14
      1552424.45      6821243.36
#Sta/Elev= 30
  4449.6 1847.17  4669.8 1840.57  4768.4 1838.44  4952.9 1837.25  4973.9  1835.5
  4998.8  1831.4  4999.3  1830.9  5005.2  1830.9  5005.7  1831.4  5007.6 1832.45
  5011.9 1832.45  5016.6  1834.3    5023 1834.42  5080.6  1834.1    5087 1832.99
    5095  1832.9  5115.8 1833.62  5123.8 1833.09  5130.2 1833.76  5137.7 1832.97
  5144.6 1833.73    5151 1833.39  5179.9 1834.66  5237.5 1834.51  5251.9 1833.71
  5279.1  1837.2  5329.7 1836.99  5386.4 1838.05  5514.5 1837.86  5802.6 1840.24
#Mann= 3 ,-1 , 0
  4449.6     .05       0  4998.8     .07       0  5005.7     .05       0
#XS Ineff= 2 , 0
       0                    5180       0    1837
Permanent Ineff=
       F       F
Bank Sta=4998.8,5005.7
XS Rating Curve= 0 ,0
Exp/Cntr=0.3,0.1

Type RM Length L Ch R = 1 ,7858    ,313,313,313
BEGIN DESCRIPTION:
Elm 01 31 7817.94
END DESCRIPTION:
XS GIS Cut Line= 3
      1551223.63      6820564.77      1551692.35      6820929.32
      1552361.27      6821449.21
#Sta/Elev= 30
  4355.7 1850.13  4451.5 1848.54  4565.5 1844.75  4594.5 1842.97  4600.8 1843.76
    4609  1842.3  4615.3 1842.88  4644.2 1840.75  4700.4 1838.93  4800.8 1836.56
  4907.6 1835.81  4914.9 1829.99  4924.8 1828.19  4925.3 1827.69  4931.9 1828.19
  4936.5 1829.36  4942.9 1829.43    4948 1833.23  4952.5 1833.23  4957.3 1831.71
  4965.5 1833.87  4971.8    1832  4978.2 1835.38  5000.8 1833.91  5036.1 1835.14
  5079.5 1834.24  5313.9 1836.61  5548.3  1837.5    5770  1840.3  5796.7 1841.61
#Mann= 3 ,-1 , 0
  4355.7    .035       0  4924.8    .035       0  4931.9    .035       0
Bank Sta=4924.8,4931.9
XS Rating Curve= 0 ,0
Exp/Cntr=0.3,0.1

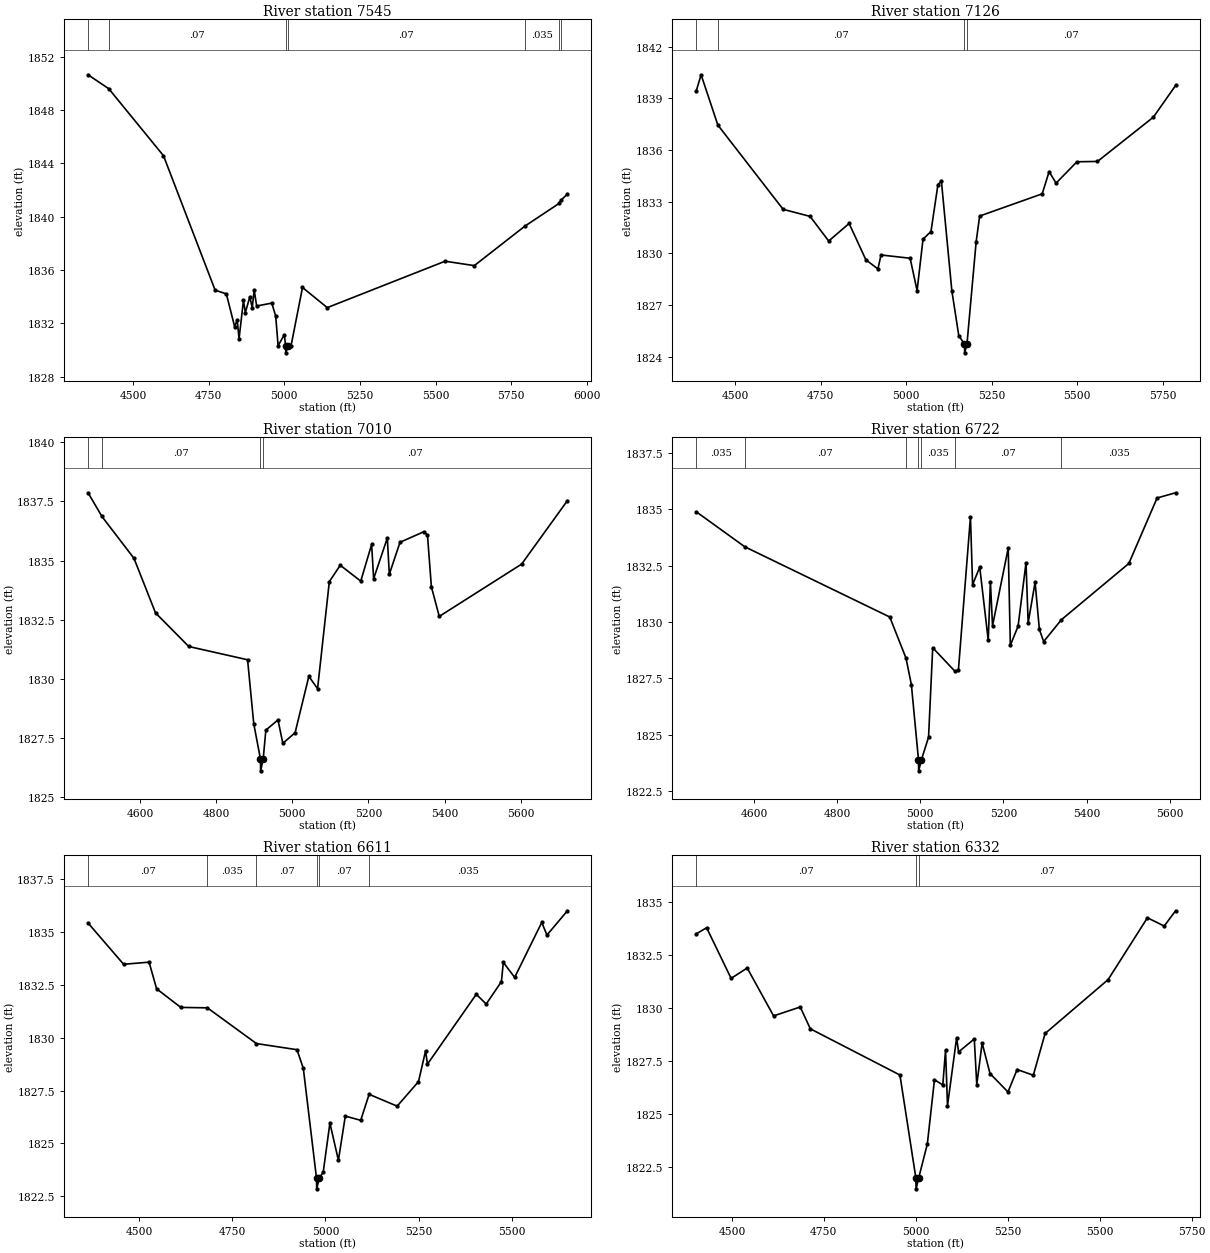
Type RM Length L Ch R = 1 ,7545    ,419,419,419
BEGIN DESCRIPTION:
Elm 01 31 7544.79
END DESCRIPTION:
XS GIS Cut Line= 3
      1551070.67      6820813.11      1551584.55        6821202.
      1552410.48      6821649.67
#Sta/Elev= 30
  4351.8 1850.65  4420.4  1849.6    4601 1844.58  4771.6  1834.5  4808.7 1834.22
  4836.1 1831.76  4844.4 1832.27  4850.7 1830.86  4865.2 1833.73  4871.5 1832.82
  4886.1 1833.99  4894.3 1833.19  4900.6 1834.51  4908.9 1833.31  4958.8 1833.53
  4971.7 1832.56  4979.7 1830.34  5000.4 1831.16  5004.6  1830.3  5005.1  1829.8
  5011.7  1830.3  5022.3 1830.31  5060.3  1834.7  5142.1 1833.19  5531.4 1836.67
    5628 1836.34  5795.1  1839.3  5908.5 1841.01  5914.2 1841.24  5935.7 1841.71
#Mann= 7 ,-1 , 0
  4351.8    .035       0  4420.4     .07       0  5004.6     .07       0
  5011.7     .07       0  5795.1    .035       0  5908.5    .063       0
  5914.2    .035       0
Bank Sta=5004.6,5011.7
XS Rating Curve= 0 ,0
Exp/Cntr=0.3,0.1

Type RM Length L Ch R = 1 ,7126    ,116,116,116
BEGIN DESCRIPTION:
Elm 01 31 7126.25
END DESCRIPTION:
XS GIS Cut Line= 3
      1550931.75      6821351.29      1551501.22      6821573.53
      1552279.02      6821712.42
#Sta/Elev= 30
  4385.9 1839.42  4400.1 1840.36  4449.1 1837.44  4639.9 1832.55  4718.7 1832.14
  4773.1 1830.71  4832.8 1831.73  4881.8 1829.62    4917 1829.09  4926.1  1829.9
  5011.2 1829.71  5031.5 1827.83  5048.9 1830.82  5072.1 1831.26  5092.5 1833.99
  5102.6 1834.18  5133.1 1827.83  5153.4 1825.22  5170.1 1824.72  5170.6 1824.22
  5177.3 1824.72  5204.2 1830.67  5214.4 1832.16  5397.3 1833.45  5417.5 1834.74
  5437.8 1834.07  5498.8 1835.31  5558.9 1835.33  5722.3  1837.9  5787.3 1839.74
#Mann= 4 ,-1 , 0
  4385.9    .035       0  4449.1     .07       0  5170.1     .07       0
  5177.3     .07       0
Bank Sta=5170.1,5177.3
XS Rating Curve= 0 ,0
Exp/Cntr=0.3,0.1

Type RM Length L Ch R = 1 ,7010    ,288,288,288
BEGIN DESCRIPTION:
Elm 01 31 7010.02
END DESCRIPTION:
XS GIS Cut Line= 3
      1550924.87      6821483.26      1551424.83      6821660.33
      1552131.58      6821837.02
#Sta/Elev= 30
  4463.8 1837.86  4500.2 1836.86  4584.4 1835.09  4640.9 1832.79  4728.2 1831.37
  4882.7 1830.81  4898.9 1828.11  4916.5 1826.62    4917 1826.12  4923.7 1826.62
  4930.7 1827.84  4962.5 1828.27  4975.3 1827.28  5007.5 1827.73  5043.6 1830.11
  5066.5 1829.59  5097.4 1834.11  5126.1  1834.8  5179.9 1834.13  5208.5 1835.68
  5213.7 1834.23  5249.7 1835.95  5254.9 1834.42    5283 1835.77  5344.8 1836.21
  5355.1 1836.08  5365.4 1833.89  5386.1 1832.64  5602.5 1834.85  5722.7 1837.53
#Mann= 4 ,-1 , 0
  4463.8    .035       0  4500.2     .07       0  4916.5     .07       0
  4923.7     .07       0
Bank Sta=4916.5,4923.7
XS Rating Curve= 0 ,0
Exp/Cntr=0.3,0.1

Type RM Length L Ch R = 1 ,6722    ,111,111,111
BEGIN DESCRIPTION:
Elm 01 31 6721.62
END DESCRIPTION:
XS GIS Cut Line= 3
      1550886.65      6821767.97      1551414.41      6821917.28
       1552004.7       6822052.7
#Sta/Elev= 30
  4460.4 1834.88  4577.2 1833.33  4926.3 1830.22  4965.4  1828.4  4978.3 1827.23
  4995.4 1823.91  4995.9 1823.41  5002.7 1823.91  5019.7  1824.9  5029.7 1828.86
  5083.7 1827.81  5091.6 1827.88  5120.6 1834.66  5125.7 1831.65  5142.9 1832.43
  5163.4 1829.19  5168.6 1831.79  5173.7 1829.83  5211.5 1833.27  5216.6 1828.97
  5235.2 1829.81  5254.3 1832.62  5259.5 1829.96  5276.2 1831.76  5286.5 1829.67
  5296.8 1829.13  5339.5  1830.1  5501.9 1832.59  5569.9 1835.49  5614.5 1835.72
#Mann= 7 ,-1 , 0
  4460.4    .035       0  4577.2     .07       0  4965.4    .035       0
  4995.4    .035       0  5002.7    .035       0  5083.7     .07       0
  5339.5    .035       0
Bank Sta=4995.4,5002.7
XS Rating Curve= 0 ,0
Exp/Cntr=0.3,0.1

Type RM Length L Ch R = 1 ,6611    ,279,279,279
BEGIN DESCRIPTION:
Elm 01 31 6528.6
END DESCRIPTION:
XS GIS Cut Line= 3
       1550772.8      6821941.06      1551387.34      6822020.92
      1552031.62      6822187.18
#Sta/Elev= 30
  4363.6 1835.42  4458.9 1833.47  4527.2 1833.57  4547.3 1832.31  4612.2 1831.43
  4683.5 1831.41    4815 1829.72  4923.7 1829.43  4940.6 1828.55    4976 1823.35
  4976.5 1822.85  4983.3 1823.35    4994 1823.64  5011.9 1825.96  5034.7  1824.2
  5053.2 1826.29  5094.5 1826.09    5117 1827.32  5192.2 1826.76  5249.4 1827.92
  5268.3 1829.37  5273.5 1828.75  5404.3 1832.05    5431 1831.59  5471.7 1832.65
  5476.8 1833.56  5507.2 1832.85  5579.9 1835.45  5593.7 1834.85  5648.7    1836
#Mann= 6 ,-1 , 0
  4363.6     .07       0  4683.5    .035       0    4815     .07       0
    4976     .07       0  4983.3     .07       0    5117    .035       0
Bank Sta=4976,4983.3
XS Rating Curve= 0 ,0
Exp/Cntr=0.3,0.1

Type RM Length L Ch R = 1 ,6332    ,253,253,253
BEGIN DESCRIPTION:
Elm 01 31 6331.59
END DESCRIPTION:
XS GIS Cut Line= 3
      1550733.84      6822104.77      1551310.25      6822274.92
      1551966.54      6822524.93
#Sta/Elev= 30
  4403.1 1833.51  4431.3  1833.8  4497.9 1831.41  4541.6  1831.9  4613.4 1829.64
  4685.8 1830.06  4713.3 1829.03  4956.9 1826.85  5000.3 1821.98  5000.8 1821.48
  5007.7 1821.98  5031.4  1823.6  5050.8 1826.63  5073.4 1826.38  5080.9 1828.02
  5086.2  1825.4    5111 1828.61  5116.3 1827.94    5159 1828.55  5165.8  1826.4
  5180.4 1828.36  5201.8 1826.92  5250.7 1826.05  5275.5 1827.11  5319.5 1826.84
  5351.6 1828.81  5522.8 1831.35  5629.8 1834.27  5675.4 1833.88  5706.4  1834.6
#Mann= 3 ,-1 , 0
  4403.1     .07       0  5000.3     .07       0  5007.7     .07       0
Bank Sta=5000.3,5007.7
XS Rating Curve= 0 ,0
Exp/Cntr=0.3,0.1

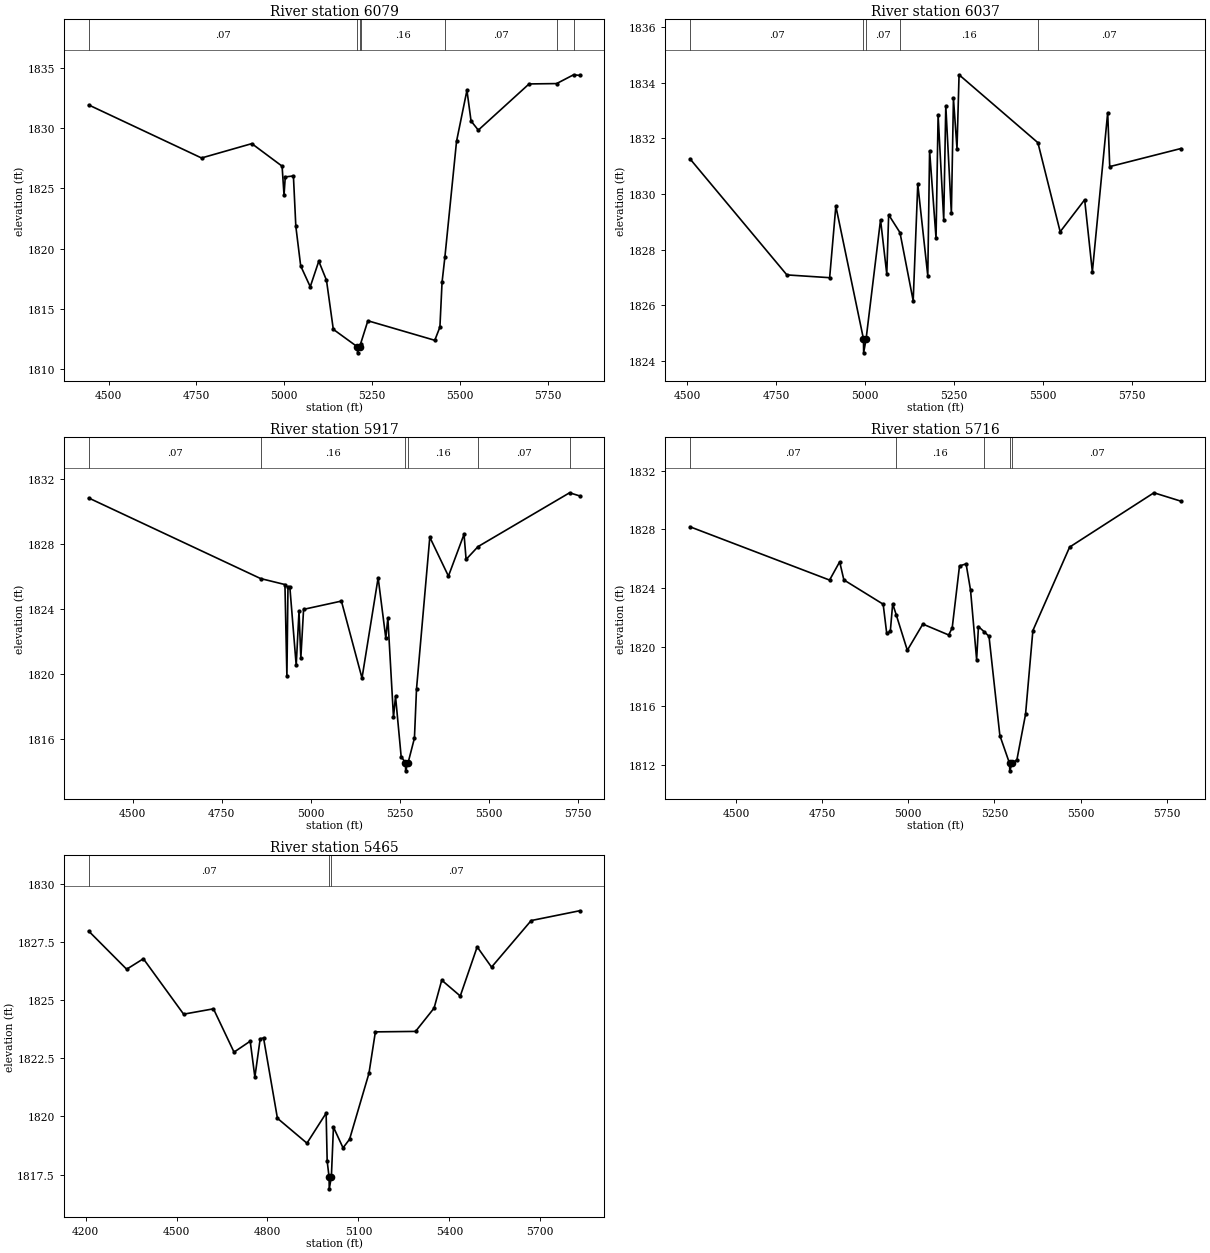
Type RM Length L Ch R = 1 ,6079    ,42,42,42
BEGIN DESCRIPTION:
Elm 01 31 6078.62
END DESCRIPTION:
XS GIS Cut Line= 3
      1550674.85      6822229.79      1551185.25      6822465.89
      1551994.25      6822670.74
#Sta/Elev= 30
  4443.4 1831.92  4764.6 1827.52  4907.7 1828.71  4993.9 1826.84  4999.4 1824.44
  5002.9 1825.95  5026.1 1826.03    5033 1821.84  5046.8 1818.57    5074 1816.84
  5098.3 1818.96  5120.2 1817.38  5139.6 1813.31  5208.1 1811.86  5208.6 1811.36
  5215.5 1811.86  5217.2  1812.1    5238 1814.02  5428.4  1812.4    5443  1813.5
  5449.1 1817.22  5457.2 1819.31  5490.3  1828.9  5519.9 1833.13  5531.6 1830.59
  5552.2 1829.83  5696.7 1833.66  5775.1 1833.69  5823.4 1834.42  5840.3 1834.37
#Mann= 7 ,-1 , 0
  4443.4     .07       0  5208.1     .07       0  5215.5     .07       0
  5217.2     .16       0  5457.2     .07       0  5775.1    .035       0
  5823.4     .07       0
Bank Sta=5208.1,5215.5
XS Rating Curve= 0 ,0
Exp/Cntr=0.3,0.1

Type RM Length L Ch R = 1 ,6037    ,120,120,120
BEGIN DESCRIPTION:
Elm 01 31 5.0
END DESCRIPTION:
XS GIS Cut Line= 4
      1550709.31      6822290.39       1551219.7      6822526.49
      1551334.29      6822555.51      1551938.98      6822905.43
#Sta/Elev= 30
  4507.5 1831.26  4779.7 1827.09  4899.9 1826.99  4917.3 1829.56  4994.9 1824.79
  4995.4 1824.29  5002.3 1824.79  5042.9 1829.07  5060.4 1827.12  5065.7 1829.25
  5097.5 1828.61  5134.6 1826.16  5147.5 1830.35  5175.6 1827.06  5180.7 1831.55
  5198.8 1828.41  5204.6 1832.83  5220.4 1829.07  5226.2 1833.17  5241.9  1829.3
  5247.7 1833.43  5257.7 1831.63  5263.5 1834.28    5485 1831.84  5547.6 1828.64
  5616.4 1829.79    5638  1827.2  5681.1 1832.92  5686.8 1830.98  5886.7 1831.63
#Mann= 5 ,-1 , 0
  4507.5     .07       0  4994.9     .07       0  5002.3     .07       0
  5097.5     .16       0    5485     .07       0
Bank Sta=4994.9,5002.3
XS Rating Curve= 0 ,0
Exp/Cntr=0.3,0.1

Type RM Length L Ch R = 1 ,5917    ,201,201,201
BEGIN DESCRIPTION:
Elm 01 31 4.5
END DESCRIPTION:
XS GIS Cut Line= 4
      1550634.94      6822349.33      1551145.34      6822585.44
      1551259.94      6822614.45      1551863.49      6822963.72
#Sta/Elev= 30
  4376.8 1830.86  4859.4 1825.89  4927.8 1825.52  4933.3 1819.85  4936.3 1825.35
  4941.6 1825.35  4959.4 1820.54  4967.3 1823.87  4972.4 1820.98  4980.1 1823.99
  5086.3  1824.5  5144.1 1819.75  5189.4 1825.94  5210.9 1822.22  5216.7 1823.45
  5232.5 1817.33  5238.2 1818.63    5254 1814.91  5266.1 1814.53  5266.6 1814.03
  5273.5 1814.53  5291.3 1816.05  5297.1 1819.08  5334.4 1828.44  5386.7 1826.04
  5430.5 1828.62  5436.3 1827.07  5469.8 1827.86  5726.8 1831.18  5754.7 1830.99
#Mann= 6 ,-1 , 0
  4376.8     .07       0  4859.4     .16       0  5266.1     .07       0
  5273.5     .16       0  5469.8     .07       0  5726.8    .035       0
Bank Sta=5266.1,5273.5
XS Rating Curve= 0 ,0
Exp/Cntr=0.3,0.1

Type RM Length L Ch R = 1 ,5716    ,251,251,251
BEGIN DESCRIPTION:
Elm 01 31 5716.07
END DESCRIPTION:
XS GIS Cut Line= 3
      1550494.27      6822597.83      1551105.38       6822764.5
      1551848.43      6823035.33
#Sta/Elev= 30
  4366.7 1828.18  4771.7 1824.56    4801  1825.8  4813.2 1824.57  4927.2 1822.92
  4937.5 1820.94  4947.9 1821.07  4954.8 1822.95  4965.1  1822.2  4997.3 1819.79
  5042.3 1821.57  5117.3 1820.83  5127.5 1821.31  5148.7 1825.52  5167.8 1825.66
  5180.7 1823.88  5198.4 1819.15  5203.7  1821.4  5219.8 1821.06  5234.3 1820.74
  5265.8    1814    5294  1812.1  5294.5  1811.6  5301.4  1812.1  5315.3 1812.36
  5340.3 1815.44  5361.6 1821.13  5468.2  1826.8  5712.8 1830.49    5791 1829.92
#Mann= 5 ,-1 , 0
  4366.7     .07       0  4965.1     .16       0  5219.8     .07       0
    5294     .07       0  5301.4     .07       0
Bank Sta=5294,5301.4
XS Rating Curve= 0 ,0
Exp/Cntr=0.3,0.1

Type RM Length L Ch R = 1 ,5465    ,345,345,345
BEGIN DESCRIPTION:
Elm 01 31 5465.11
END DESCRIPTION:
XS GIS Cut Line= 3
      1550331.11      6822663.82      1551046.36      6822993.67
      1551827.65       6823278.4
#Sta/Elev= 30
  4210.2 1827.96  4335.6 1826.32  4390.7 1826.77  4523.5 1824.39  4621.9 1824.62
  4689.7 1822.76  4743.1 1823.23  4758.5 1821.69    4776 1823.33  4787.1 1823.37
  4832.9 1819.92  4930.3 1818.85  4993.5 1820.14    4997 1818.08  5003.3 1817.39
  5003.8 1816.89  5010.8 1817.39  5017.7 1819.54  5049.3 1818.65  5070.9 1819.02
  5134.8 1821.85    5156 1823.63  5288.5 1823.65  5349.6 1824.65  5374.9 1825.85
    5436 1825.17  5491.8 1827.28  5539.2 1826.41  5669.9 1828.41  5829.4 1828.83
#Mann= 3 ,-1 , 0
  4210.2     .07       0  5003.3     .07       0  5010.8     .07       0
Bank Sta=5003.3,5010.8
XS Rating Curve= 0 ,0
Exp/Cntr=0.3,0.1