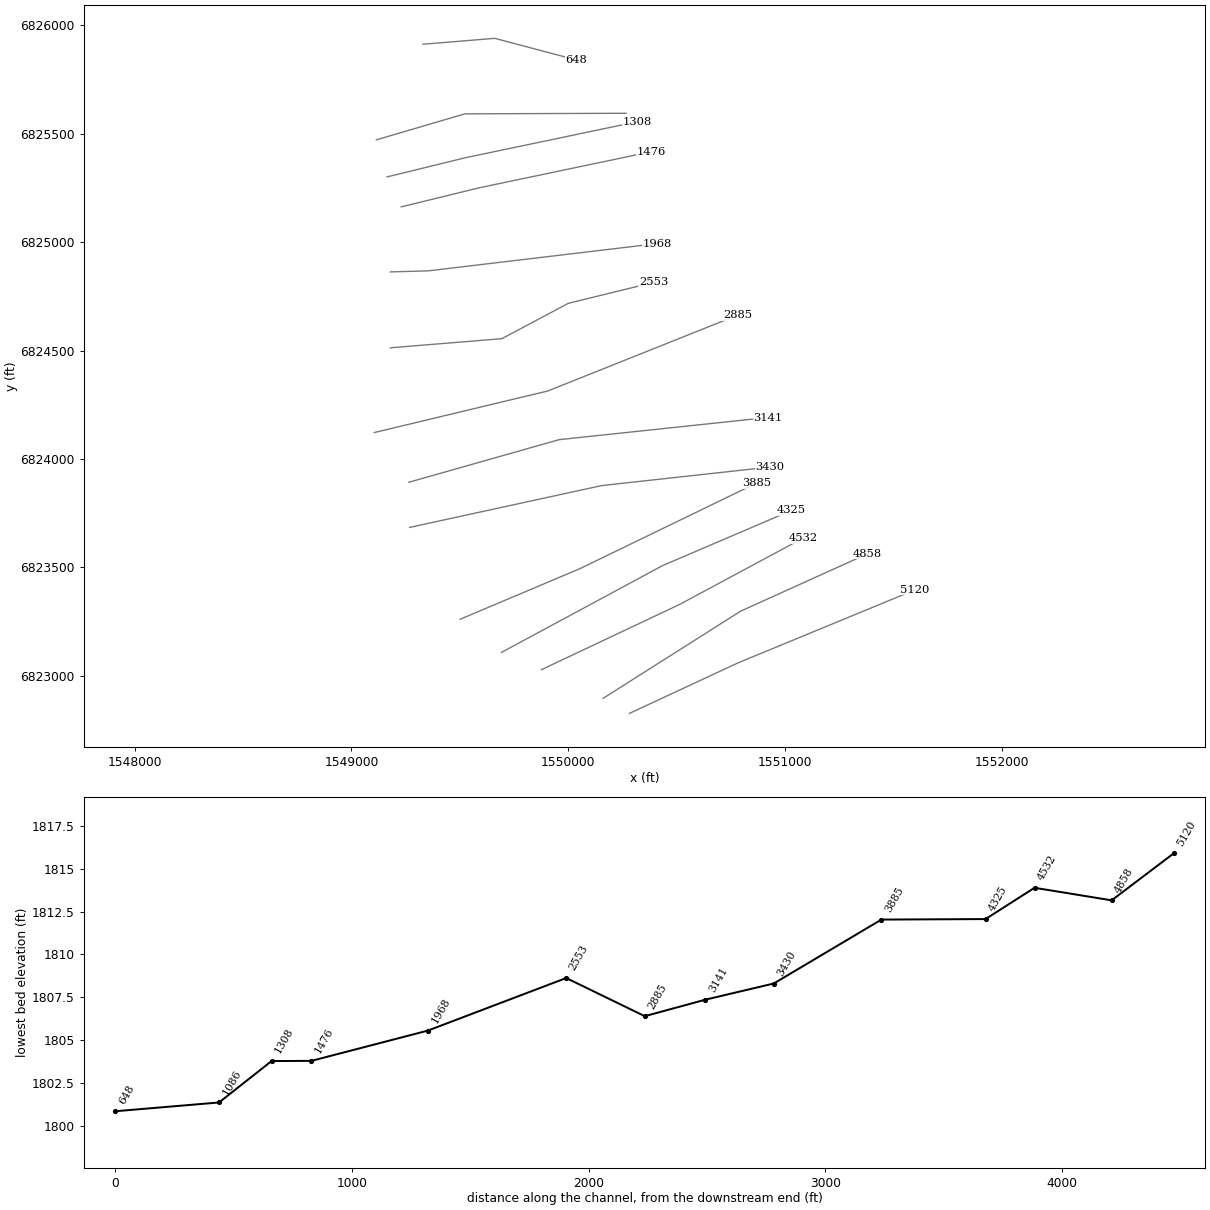
HEC-RAS study Elm 01 31.prj: Elm 01 31 Base Level Engineering

--- Elm 01 31.g01 (geometry) --- (continued)

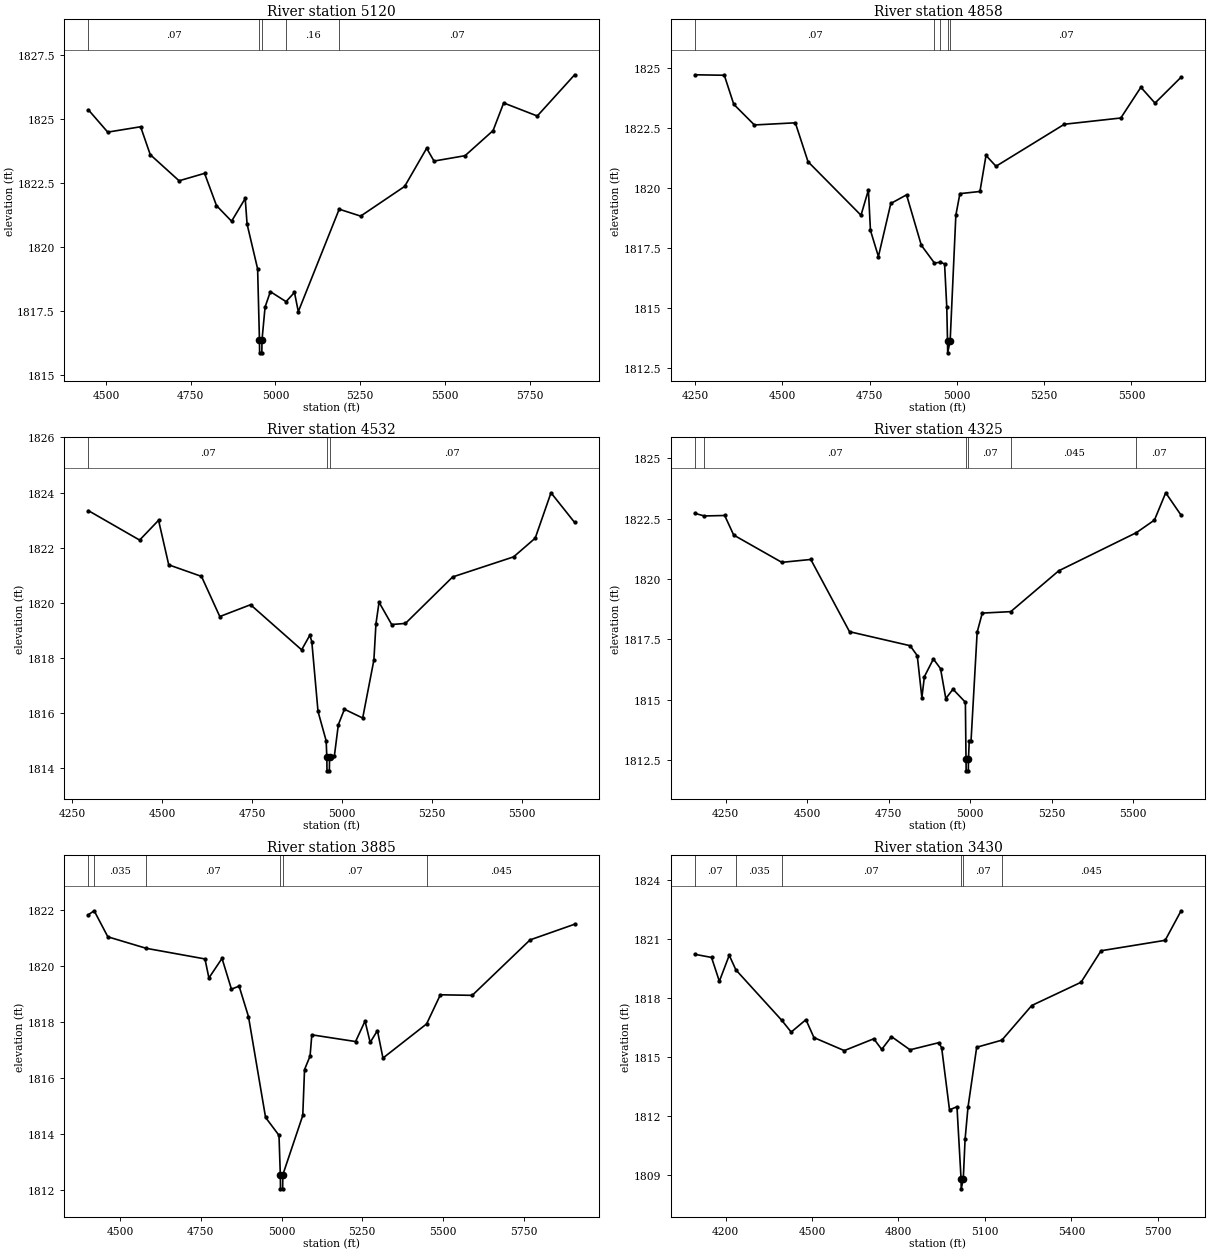
Type RM Length L Ch R = 1 ,5120    ,262,262,262
BEGIN DESCRIPTION:
Elm 01 31 5119.94
END DESCRIPTION:
XS GIS Cut Line= 3
      1550282.51      6822827.02      1550782.47      6823059.64
      1551598.46      6823396.45
#Sta/Elev= 30
  4448.4 1825.37  4505.4  1824.5  4602.4 1824.71  4630.8 1823.62  4715.9  1822.6
    4791 1822.89  4826.2 1821.63  4870.7 1821.02  4910.9 1821.91  4916.4 1820.91
  4947.5 1819.16  4952.9 1816.38  4953.4 1815.88  4959.9 1815.88  4960.4 1816.38
  4969.5 1817.67  4985.1 1818.27  5031.4 1817.88  5056.2 1818.24  5067.5 1817.49
  5188.1 1821.49  5251.4 1821.22  5381.2 1822.38  5446.1 1823.87  5467.8 1823.37
  5559.4 1823.58    5642 1824.56  5673.3 1825.64  5772.4 1825.13  5882.6 1826.74
#Mann= 5 ,-1 , 0
  4448.4     .07       0  4952.9     .07       0  4960.4     .07       0
  5031.4     .16       0  5188.1     .07       0
Bank Sta=4952.9,4960.4
XS Rating Curve= 0 ,0
Exp/Cntr=0.3,0.1

Type RM Length L Ch R = 1 ,4858    ,326,326,326
BEGIN DESCRIPTION:
Elm 01 31 4858.355
END DESCRIPTION:
XS GIS Cut Line= 3
      1550160.98      6822896.47      1550794.68      6823298.18
      1551379.97      6823562.99
#Sta/Elev= 30
  4249.7 1824.73    4334 1824.71  4361.1  1823.5  4420.2 1822.64  4537.4 1822.73
  4573.8 1821.11  4725.5 1818.88  4746.7 1819.93  4752.6 1818.25  4775.4 1817.16
  4810.9 1819.37    4856 1819.73  4898.3 1817.63  4935.9 1816.89    4951 1816.92
  4964.9 1816.86  4971.2 1815.05  4973.3 1813.65  4973.8 1813.15  4980.9 1813.65
  4997.2 1818.88  5008.8 1819.78  5066.2 1819.87  5083.6 1821.37  5112.2 1820.92
    5308 1822.67  5469.7 1822.93  5527.2 1824.21  5567.6 1823.55  5642.4 1824.63
#Mann= 5 ,-1 , 0
  4249.7     .07       0  4935.9     .16       0    4951     .07       0
  4973.3     .07       0  4980.9     .07       0
Bank Sta=4973.3,4980.9
XS Rating Curve= 0 ,0
Exp/Cntr=0.3,0.1

Type RM Length L Ch R = 1 ,4532    ,207,207,207
BEGIN DESCRIPTION:
Elm 01 31 4532.046
END DESCRIPTION:
XS GIS Cut Line= 3
      1549876.18      6823028.37      1550514.12      6823329.63
      1551084.54      6823636.02
#Sta/Elev= 30
  4294.5 1823.34    4437 1822.27  4489.7 1822.99    4518 1821.37  4609.1 1820.95
  4660.1 1819.49  4745.7 1819.92  4887.8 1818.28  4910.6 1818.81  4916.1 1818.58
  4933.4 1816.04  4956.1 1814.97  4957.9 1814.38  4958.4 1813.88    4965 1813.88
  4965.5 1814.38  4978.8 1814.41    4990 1815.56  5006.9 1816.12  5057.7  1815.8
  5088.9 1817.91  5094.6 1819.22  5103.2 1820.01  5138.4  1819.2  5176.6 1819.24
  5308.1 1820.93  5477.7 1821.66  5537.8 1822.34  5581.7 1823.99  5647.5 1822.91
#Mann= 3 ,-1 , 0
  4294.5     .07       0  4957.9     .07       0  4965.5     .07       0
Bank Sta=4957.9,4965.5
XS Rating Curve= 0 ,0
Exp/Cntr=0.3,0.1

Type RM Length L Ch R = 1 ,4325    ,440,440,440
BEGIN DESCRIPTION:
Elm 01 31 4325.1
END DESCRIPTION:
XS GIS Cut Line= 3
      1549692.17      6823108.24      1550435.53      6823508.75
      1551030.04      6823763.02
#Sta/Elev= 30
  4155.6 1822.72  4184.3 1822.61    4247 1822.63  4274.6 1821.82  4422.2 1820.69
    4511 1820.81  4629.8 1817.82  4815.6 1817.24  4837.5 1816.83  4851.7 1815.09
  4859.4 1815.96    4887 1816.69  4908.9 1816.29  4925.1 1815.05    4947 1815.44
  4985.1  1814.9    4987 1812.56  4987.5 1812.06  4994.1 1812.06  4994.6 1812.56
  4996.9 1813.29  5002.4 1813.29  5021.2  1817.8  5036.9 1818.59  5124.2 1818.65
  5271.3 1820.34  5509.5 1821.92  5564.9 1822.44  5599.4 1823.57  5646.6 1822.64
#Mann= 6 ,-1 , 0
  4155.6    .035       0  4184.3     .07       0    4987     .07       0
  4994.6     .07       0  5124.2    .045       0  5509.5     .07       0
Bank Sta=4987,4994.6
XS Rating Curve= 0 ,0
Exp/Cntr=0.3,0.1

Type RM Length L Ch R = 1 ,3885    ,455,455,455
BEGIN DESCRIPTION:
Elm 01 31 3885.165
END DESCRIPTION:
XS GIS Cut Line= 3
      1549501.19      6823261.01      1550052.38      6823493.73
      1550869.25      6823889.49
#Sta/Elev= 30
  4401.7 1821.82  4419.5 1821.96  4461.9 1821.03  4580.6 1820.62  4762.7 1820.24
  4774.9 1819.56  4815.5 1820.26  4844.7 1819.16  4868.4 1819.27  4897.5 1818.18
  4950.4 1814.58    4992 1813.94  4996.1 1812.53  4996.6 1812.03  5003.3 1812.03
  5003.8 1812.53  5065.6 1814.65  5071.1 1816.29  5088.2 1816.77  5093.7 1817.53
  5229.2 1817.29  5258.5 1818.02  5274.4 1817.26  5296.9 1817.68    5314  1816.7
  5449.2 1817.92  5491.8 1818.96  5590.5 1818.94  5769.6 1820.92  5907.7 1821.48
#Mann= 6 ,-1 , 0
  4401.7     .07       0  4419.5    .035       0  4580.6     .07       0
  4996.1     .07       0  5003.8     .07       0  5449.2    .045       0
Bank Sta=4996.1,5003.8
XS Rating Curve= 0 ,0
Exp/Cntr=0.3,0.1

Type RM Length L Ch R = 1 ,3430    ,289,289,289
BEGIN DESCRIPTION:
Elm 01 31 3430.494
END DESCRIPTION:
XS GIS Cut Line= 3
      1549268.53      6823684.63      1550154.07      6823877.52
      1550929.97        6823963.
#Sta/Elev= 30
  4093.7 1820.22  4151.5 1820.06  4178.6 1818.85  4212.9 1820.17  4235.9 1819.43
    4395 1816.87  4427.8 1816.27    4479  1816.9  4506.8 1815.99    4612 1815.33
  4714.4 1815.93  4741.9 1815.39  4775.8 1816.04  4840.1 1815.37  4939.5 1815.73
  4949.8 1815.48  4977.1 1812.32    5003 1812.48  5017.2 1808.81  5017.7 1808.31
  5024.9 1808.81  5031.1 1810.82  5041.2 1812.45  5071.4  1815.5  5158.7 1815.86
  5262.5 1817.62  5433.5  1818.8  5502.8  1820.4  5725.3 1820.93  5780.6 1822.43
#Mann= 6 ,-1 , 0
  4093.7     .07       0  4235.9    .035       0    4395     .07       0
  5017.2     .07       0  5024.9     .07       0  5158.7    .045       0
Bank Sta=5017.2,5024.9
XS Rating Curve= 0 ,0
Exp/Cntr=0.3,0.1

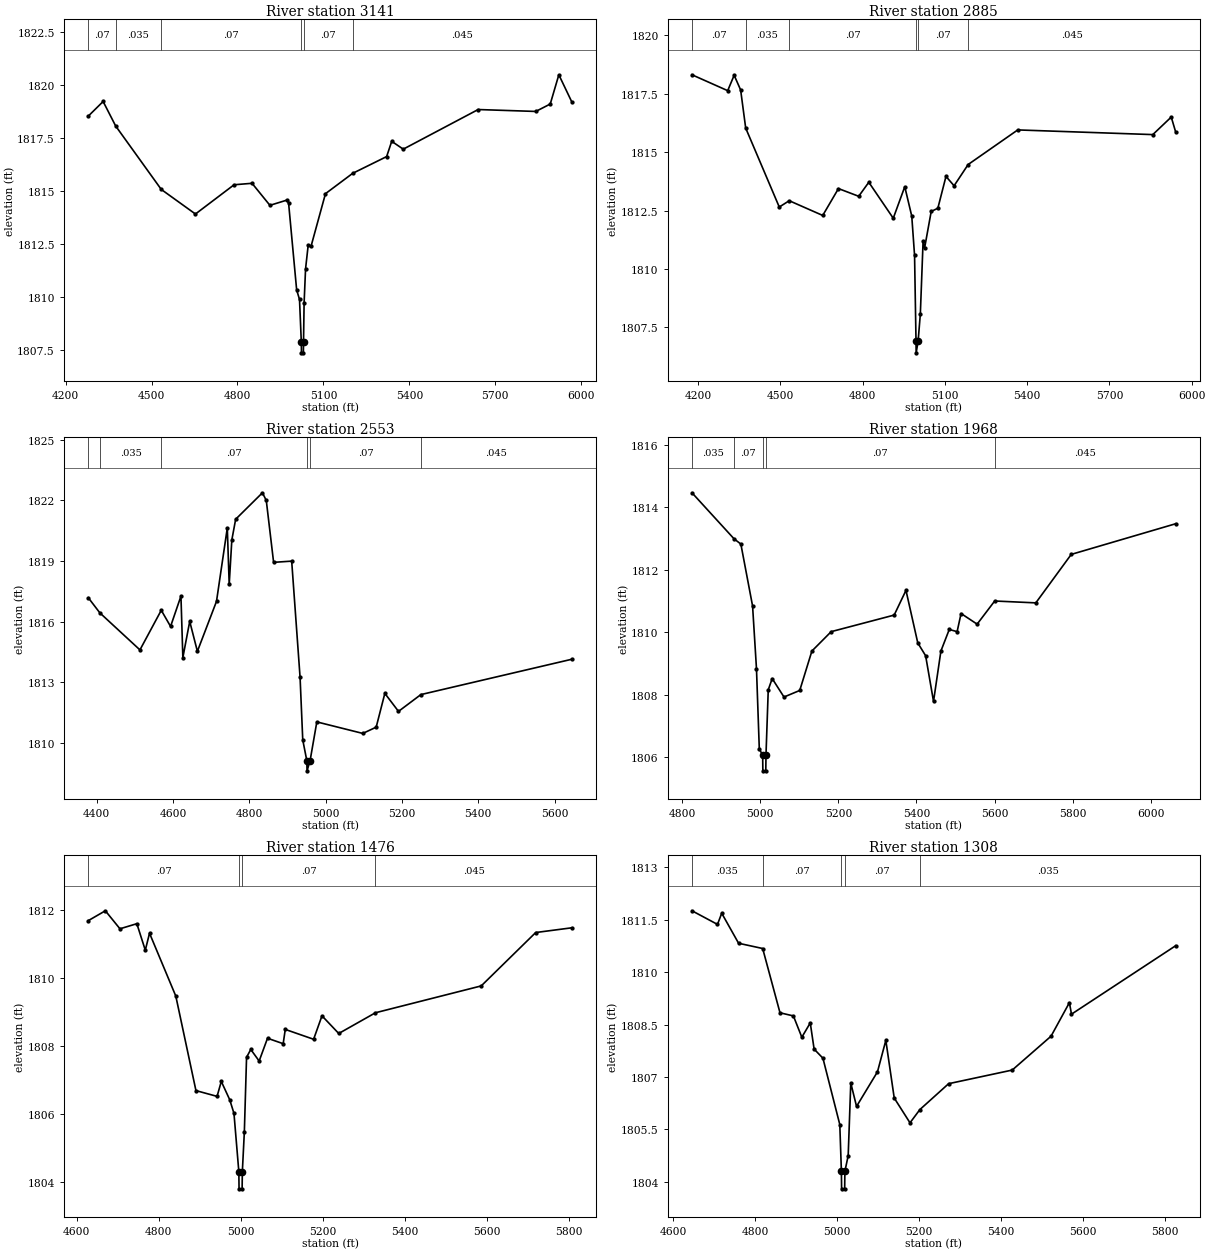
Type RM Length L Ch R = 1 ,3141    ,256,256,256
BEGIN DESCRIPTION:
Elm 01 31 3140.578
END DESCRIPTION:
XS GIS Cut Line= 3
      1549265.15      6823892.98      1549958.55      6824089.47
      1550920.65      6824191.51
#Sta/Elev= 30
  4279.3 1818.54  4331.1 1819.23    4375 1818.07    4534 1815.08  4653.3 1813.92
  4788.1  1815.3  4850.8 1815.37  4913.2 1814.33  4973.3 1814.58  4978.5 1814.42
  5006.5 1810.34  5016.5 1809.89  5022.8 1807.87  5023.3 1807.37    5030 1807.37
  5030.5 1807.87  5032.5 1809.71  5037.6 1811.33  5046.7 1812.44  5056.8  1812.4
  5107.1 1814.88  5202.1 1815.84  5320.6 1816.63  5338.3 1817.35  5378.6 1816.98
    5640 1818.85  5841.1 1818.76  5891.6 1819.11  5921.6 1820.49  5967.5 1819.19
#Mann= 6 ,-1 , 0
  4279.3     .07       0    4375    .035       0    4534     .07       0
  5022.8     .07       0  5030.5     .07       0  5202.1    .045       0
Bank Sta=5022.8,5030.5
XS Rating Curve= 0 ,0
Exp/Cntr=0.3,0.1

Type RM Length L Ch R = 1 ,2885    ,332,332,332
BEGIN DESCRIPTION:
Elm 01 31 2885.129
END DESCRIPTION:
XS GIS Cut Line= 3
      1549105.39      6824122.14      1549905.37      6824313.73
      1550780.01        6824663.
#Sta/Elev= 30
  4177.4 1818.31  4307.7 1817.63  4331.2 1818.29  4354.9 1817.66  4373.3 1816.03
  4495.8 1812.65  4532.2 1812.92  4654.3 1812.29  4711.7 1813.44  4785.5 1813.11
  4822.4 1813.71  4911.6 1812.17  4953.6 1813.52  4979.1 1812.26  4989.3 1810.58
  4994.6 1806.91  4995.1 1806.41  5002.3 1806.91  5010.4 1808.08  5020.4 1811.18
  5025.8 1810.89    5050 1812.46  5074.3  1812.6  5103.9 1813.96  5133.5 1813.56
  5184.8 1814.47  5365.7 1815.95  5858.3 1815.75  5925.6  1816.5  5941.8 1815.86
#Mann= 6 ,-1 , 0
  4177.4     .07       0  4373.3    .035       0  4532.2     .07       0
  4994.6     .07       0  5002.3     .07       0  5184.8    .045       0
Bank Sta=4994.6,5002.3
XS Rating Curve= 0 ,0
Exp/Cntr=0.3,0.1

Type RM Length L Ch R = 1 ,2553    ,585,585,585
BEGIN DESCRIPTION:
Elm 01 31 2184.046
END DESCRIPTION:
XS GIS Cut Line= 4
        1549180.        6824513.      1549693.95      6824555.09
      1550000.61      6824718.19      1550393.96      6824814.64
#Sta/Elev= 30
  4377.7 1817.19  4408.1 1816.44  4513.1 1814.61    4569 1816.57  4593.4 1815.77
  4620.6 1817.27  4625.6 1814.23  4643.6 1816.02  4663.7 1814.54  4713.8 1817.01
  4742.1 1820.64  4747.1 1817.85    4754 1820.05    4764 1821.07  4834.2 1822.38
  4844.3    1822  4863.5 1818.94  4910.9    1819  4932.9 1813.25  4939.9 1810.16
  4950.6 1809.13  4951.1 1808.63  4959.1 1809.13  4976.8 1811.05  5097.3 1810.48
  5132.4 1810.79  5155.1 1812.46  5190.9 1811.57  5249.5  1812.4  5645.7 1814.15
#Mann= 6 ,-1 , 0
  4377.7     .07       0  4408.1    .035       0    4569     .07       0
  4950.6     .07       0  4959.1     .07       0  5249.5    .045       0
Bank Sta=4950.6,4959.1
XS Rating Curve= 0 ,0
Exp/Cntr=0.3,0.1

Type RM Length L Ch R = 1 ,1968    ,492,492,492
BEGIN DESCRIPTION:
Elm 01 31 1967.816
END DESCRIPTION:
XS GIS Cut Line= 3
        1549180.        6824863.      1549354.53      6824867.84
      1550410.47      6824993.61
#Sta/Elev= 30
  4825.4 1814.46  4932.9 1812.99  4950.5 1812.82  4980.5 1810.84  4990.5 1808.83
  4997.7 1806.27  5006.3 1806.07  5006.8 1805.57  5014.3 1805.57  5014.8 1806.07
  5020.6 1808.16  5030.7 1808.52  5060.9 1807.93  5101.2 1808.14  5132.3  1809.4
  5181.7 1810.02  5342.9 1810.55  5373.1 1811.34  5403.3 1809.66  5423.4 1809.25
  5443.6 1807.79  5462.5  1809.4  5483.9 1810.09    5504 1810.02  5514.1  1810.6
  5555.2 1810.26  5600.2    1811  5705.4 1810.94  5796.1 1812.49  6063.4 1813.47
#Mann= 5 ,-1 , 0
  4825.4    .035       0  4932.9     .07       0  5006.3     .07       0
  5014.8     .07       0  5600.2    .045       0
Bank Sta=5006.3,5014.8
XS Rating Curve= 0 ,0
Exp/Cntr=0.3,0.1

Type RM Length L Ch R = 1 ,1476    ,168,168,168
BEGIN DESCRIPTION:
Elm 01 31 1476.122
END DESCRIPTION:
XS GIS Cut Line= 3
        1549230.        6825163.      1549591.46      6825251.35
      1550381.59      6825416.95
#Sta/Elev= 30
  4627.9  1811.7  4669.5 1811.99  4705.1 1811.46  4746.3 1811.61  4766.9 1810.83
  4777.2 1811.33  4841.3 1809.48  4890.4  1806.7  4941.9 1806.53  4952.2 1806.97
  4972.8 1806.43  4983.1 1806.03    4995 1804.31  4995.5 1803.81    5003 1803.81
  5003.5 1804.31  5008.4 1805.48  5013.8 1807.68  5024.1 1807.91  5044.5 1807.57
  5064.9 1808.24  5103.1 1808.08  5108.2  1808.5  5177.3 1808.21  5197.7  1808.9
  5238.6 1808.38  5328.1 1808.99    5586 1809.78  5718.8 1811.35  5807.3 1811.49
#Mann= 4 ,-1 , 0
  4627.9     .07       0    4995     .07       0  5003.5     .07       0
  5328.1    .045       0
Bank Sta=4995,5003.5
XS Rating Curve= 0 ,0
Exp/Cntr=0.3,0.1

Type RM Length L Ch R = 1 ,1308    ,222,222,222
BEGIN DESCRIPTION:
Elm 01 31 1.0
END DESCRIPTION:
XS GIS Cut Line= 3
      1549164.45       6825301.2      1549525.91      6825389.55
      1550317.61      6825555.47
#Sta/Elev= 30
  4646.2 1811.76  4708.5 1811.37  4718.8 1811.69    4760 1810.83  4818.8 1810.68
  4861.1 1808.84  4893.8 1808.75  4914.4 1808.14    4935 1808.55  4944.4  1807.8
  4965.9 1807.54  5007.1 1805.64    5011  1804.3  5011.5  1803.8    5019  1803.8
  5019.5  1804.3  5027.6 1804.75  5033.9 1806.83    5048 1806.16  5099.1 1807.15
  5119.5 1808.05    5140  1806.4  5178.5 1805.69  5202.7 1806.07  5272.8 1806.81
  5428.1  1807.2  5522.9 1808.17  5567.7 1809.13  5572.8  1808.8  5827.2 1810.76
#Mann= 5 ,-1 , 0
  4646.2    .035       0  4818.8     .07       0    5011     .07       0
  5019.5     .07       0  5202.7    .035       0
Bank Sta=5011,5019.5
XS Rating Curve= 0 ,0
Exp/Cntr=0.3,0.1

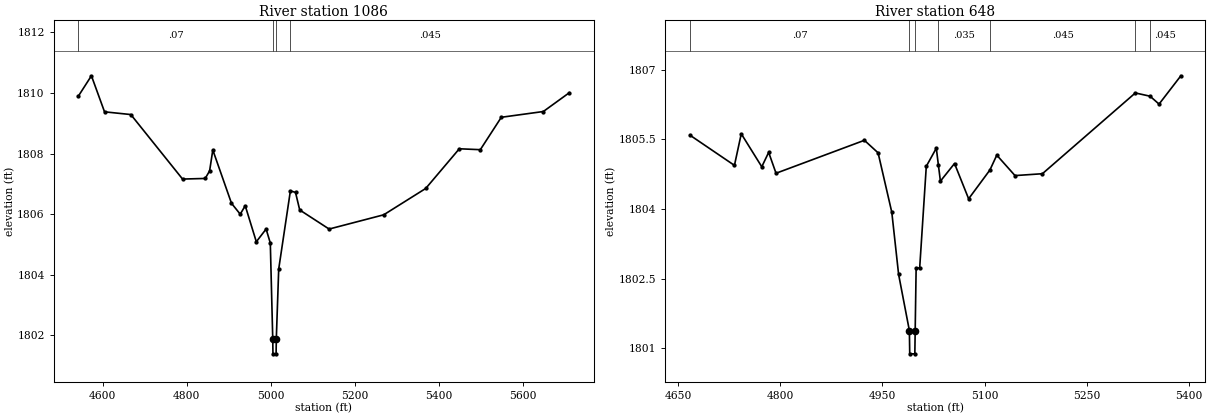
Type RM Length L Ch R = 1 ,1086    ,438,438,438
BEGIN DESCRIPTION:
Elm 01 31 1154.397
END DESCRIPTION:
XS GIS Cut Line= 3
       1549115.3      6825472.14      1549523.45        6825592.
      1550266.76      6825594.62
#Sta/Elev= 30
  4542.6  1809.9  4573.6 1810.57  4604.8 1809.38  4667.4 1809.29  4790.6 1807.16
  4844.5 1807.18    4855 1807.43  4862.6 1808.12  4907.1 1806.36  4927.9    1806
  4939.8 1806.28  4966.2 1805.09  4989.5 1805.51  4999.5 1805.05  5005.3 1801.89
  5005.8 1801.39  5013.3 1801.39  5013.8 1801.89  5019.5 1804.19  5047.3 1806.77
  5059.5 1806.72  5069.5 1806.14  5139.5 1805.51  5269.5 1805.98  5369.5 1806.85
  5449.5 1808.16  5499.5 1808.13  5549.5  1809.2  5649.5 1809.39  5711.3 1810.01
#Mann= 4 ,-1 , 0
  4542.6     .07       0  5005.3     .07       0  5013.8     .07       0
  5047.3    .045       0
Bank Sta=5005.3,5013.8
XS Rating Curve= 0 ,0
Exp/Cntr=0.3,0.1

Type RM Length L Ch R = 1 ,648     ,0,0,0
BEGIN DESCRIPTION:
Elm 01 31 648.351
END DESCRIPTION:
XS GIS Cut Line= 3
      1549330.01        6825913.       1549661.2      6825940.22
      1550035.95      6825840.88
#Sta/Elev= 30
  4667.7 1805.59  4732.9 1804.94  4742.9 1805.62    4773 1804.91  4783.1 1805.22
  4793.9 1804.77  4923.5 1805.48  4943.6 1805.21  4963.7 1803.93  4973.7 1802.59
  4989.5 1801.38    4990 1800.88  4997.5 1800.88    4998 1801.38  4999.4 1802.73
  5004.6 1802.73  5014.3 1804.92    5029 1805.31  5032.1 1804.94    5035  1804.6
  5055.7 1804.98  5076.4 1804.22  5107.6 1804.84  5117.7 1805.16  5144.4 1804.72
  5184.6 1804.76  5320.9  1806.5  5342.5 1806.43  5355.7 1806.26  5387.7 1806.87
#Mann= 7 ,-1 , 0
  4667.7     .07       0  4989.5     .07       0    4998     .07       0
  5032.1    .035       0  5107.6    .045       0  5320.9    .035       0
  5342.5    .045       0
Bank Sta=4989.5,4998
XS Rating Curve= 0 ,0
Exp/Cntr=0.3,0.1

Chan Stop Cuts=-1
Use User Specified Reach Order=0
Composite Channel Slope=5