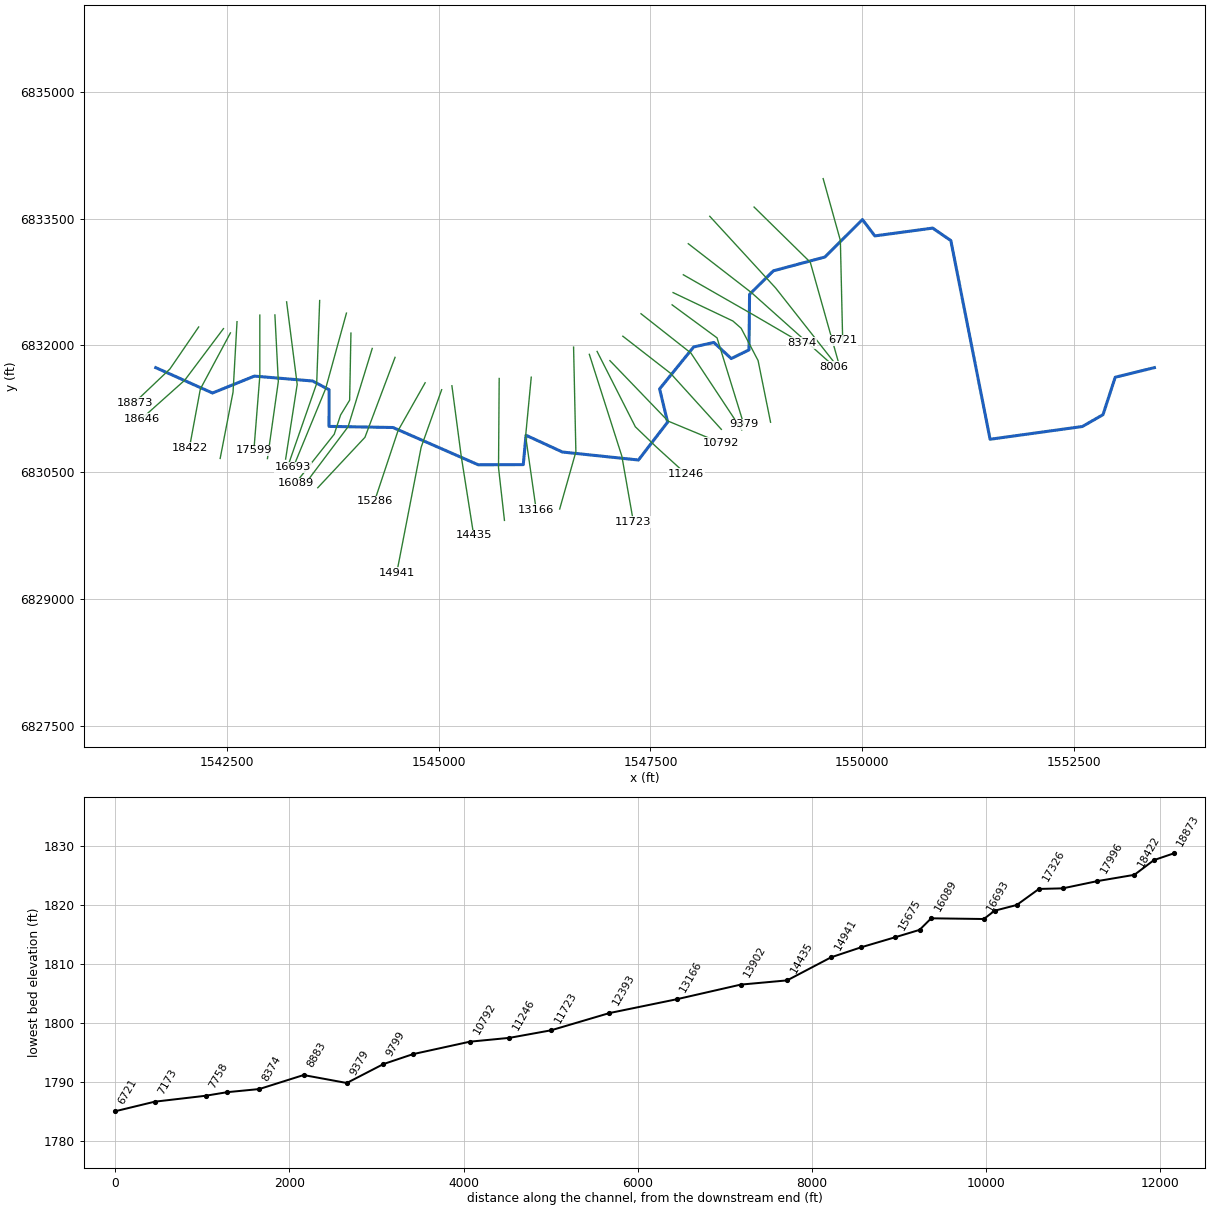
--- Elm 01 32.prj (project) ---

Proj Title=Elm 01 32 Base Level Engineering
Current Plan=p01
Default Exp/Contr=0.3,0.1
English Units
Geom File=g01
Flow File=f01
Plan File=p01
BEGIN DESCRIPTION:
Elm 01 32
END DESCRIPTION:

--- Elm 01 32.p01 (plan) ---

Plan Title=Multiple Run
Short Identifier=Multiple
Geom File=g01
Flow File=f01
Subcritical Flow
K Sum by GR= 0
Std Step Tol= 0.01
Critical Tol= 0.01
Num of Std Step Trials= 20
Max Error Tol= 0.3
Flow Tol Ratio= 0.001
Split Flow NTrial= 30
Split Flow Tol= 0.02
Split Flow Ratio= 0.02
Log Output Level= 0
Friction Slope Method= 1
Unsteady Friction Slope Method= 2
Unsteady Bridges Friction Slope Method= 1
Parabolic Critical Depth
Global Vel Dist=  1 , 1 , 1
Global Log Level= 0
CheckData=True
Encroach Param= -1, 0, 0, 0
BEGIN DESCRIPTION:
Multiple Run
END DESCRIPTION:

--- Elm 01 32.f01 (steady flow) ---

Flow Title=Multiple
Number of Profiles=7
Profile Names=10-year,25-year,50-year,1pct_min,100-year,1pct_plu,500-year
River Rch & RM= Elm 01 32,Reach-1,18873
     158     214     260     196     313     431     463
River Rch & RM= Elm 01 32,Reach-1,18422
     294     413     512     394     632     870     975
River Rch & RM= Elm 01 32,Reach-1,14435
     386     546     681     526     843    1160    1310
River Rch & RM= Elm 01 32,Reach-1,7758
     424     598     744     572     917    1260    1410
Boundary for River Rch & Prof#=Elm 01 32,Reach-1,1
Up Type=0
Dn Type=3
Dn Slope=0.005
Boundary for River Rch & Prof#=Elm 01 32,Reach-1,2
Up Type=0
Dn Type=3
Dn Slope=0.005
Boundary for River Rch & Prof#=Elm 01 32,Reach-1,3
Up Type=0
Dn Type=3
Dn Slope=0.005
Boundary for River Rch & Prof#=Elm 01 32,Reach-1,4
Up Type=0
Dn Type=3
Dn Slope=0.005
Boundary for River Rch & Prof#=Elm 01 32,Reach-1,5
Up Type=0
Dn Type=3
Dn Slope=0.005
Boundary for River Rch & Prof#=Elm 01 32,Reach-1,6
Up Type=0
Dn Type=3
Dn Slope=0.005
Boundary for River Rch & Prof#=Elm 01 32,Reach-1,7
Up Type=0
Dn Type=3
Dn Slope=0.005

--- Elm 01 32.g01 (geometry) ---

Geom Title=Existing Conditions

River Reach=Elm 01 32,Reach-1
Reach XY= 30
      1541655.00      6831738.00      1542325.10      6831437.91
      1542820.22      6831637.75      1543508.32      6831579.96
      1543703.38      6831476.19      1543702.22      6831043.36
      1544458.32      6831029.96      1545465.53      6830589.08
      1545997.46      6830591.06      1546029.70      6830938.30
      1546460.65      6830739.97      1547358.41      6830645.81
      1547703.02      6831093.67      1547608.13      6831486.36
      1548010.61      6831982.41      1548249.09      6832035.78
      1548454.98      6831845.08      1548664.83      6831948.52
      1548671.17      6832604.58      1548952.55      6832882.53
      1549561.17      6833045.86      1550005.03      6833488.89
      1550151.30      6833295.68      1550834.97      6833387.94
      1551049.55      6833240.47      1551513.28      6830891.06
      1552603.45      6831041.75      1552847.31      6831181.52
      1552991.78      6831624.38      1553455.00      6831738.00

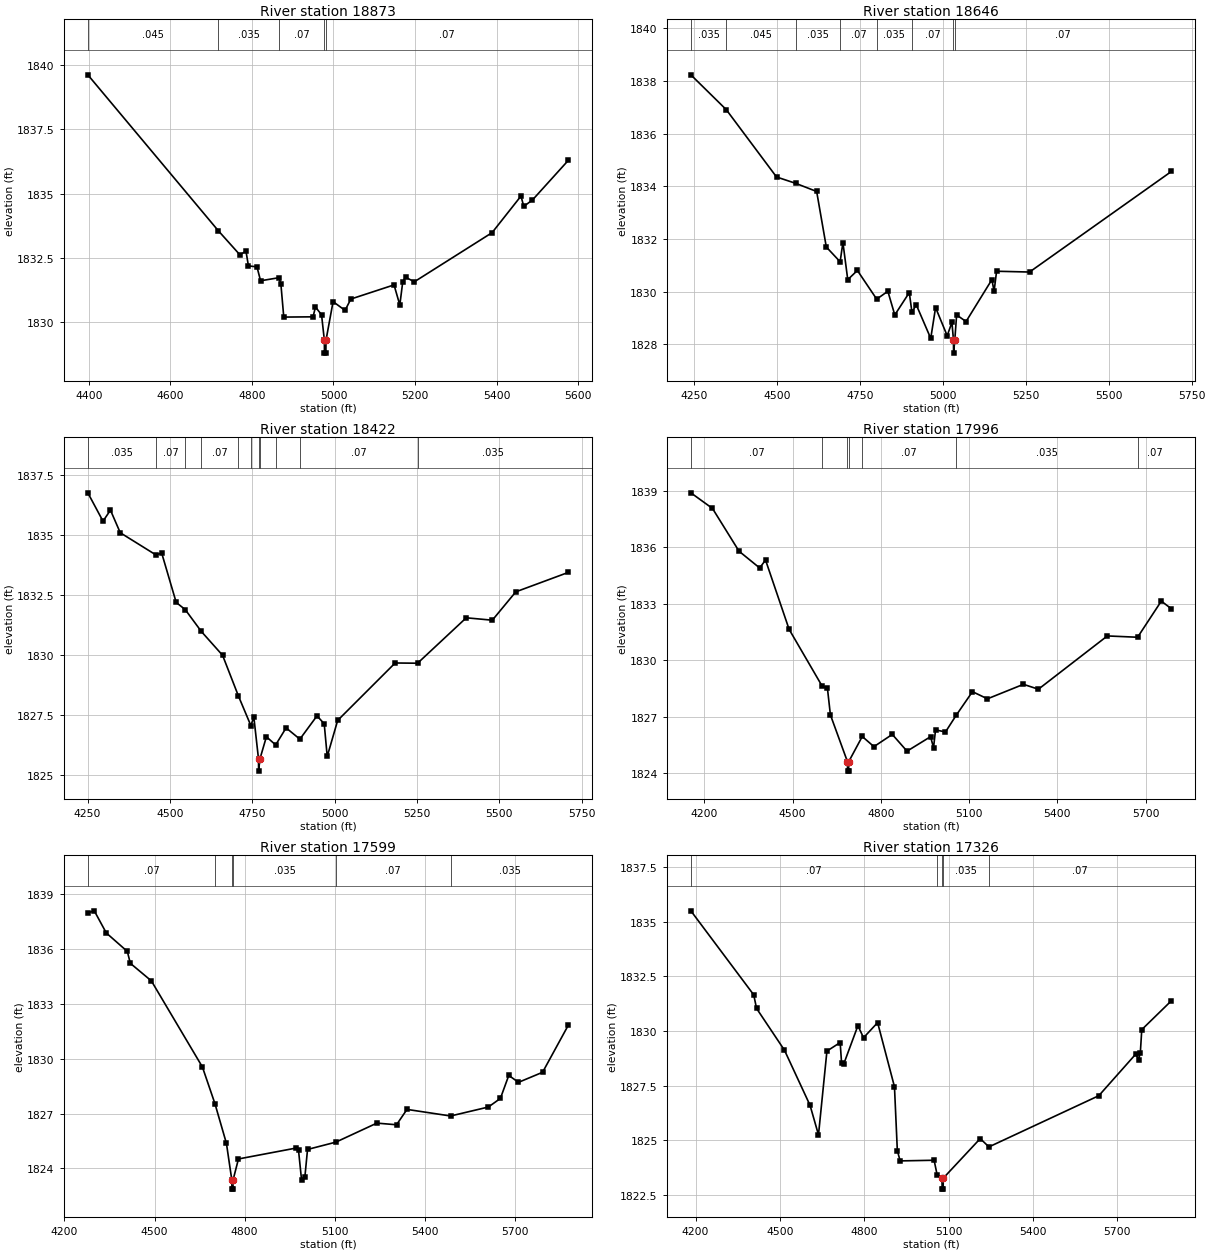
Type RM Length L Ch R = 1,18873,227,227,227
BEGIN DESCRIPTION:
Elm 01 32 18872.654
END DESCRIPTION:
XS GIS Cut Line= 3
      1542162.00      6832218.89      1541821.75      6831721.54
      1541404.18      6831324.36
#Sta/Elev= 30
  4397.4 1839.62  4717.2 1833.57  4770.4 1832.63  4785.4 1832.77  4791.4 1832.20
  4812.4 1832.16  4821.2 1831.62  4866.4 1831.74  4871.0 1831.50  4878.1 1830.21
  4949.9 1830.22  4955.9 1830.60  4970.8 1830.30  4977.7 1829.31  4977.9 1828.81
  4981.4 1828.81  4981.7 1829.31  4999.1 1830.81  5028.5 1830.47  5042.6 1830.91
  5148.6 1831.46  5162.8 1830.68  5170.0 1831.58  5176.9 1831.76  5198.3 1831.58
  5389.2 1833.49  5460.0 1834.91  5466.9 1834.51  5488.3 1834.76  5576.3 1836.30
#Mann=5,-1,0
  4397.4   0.045       0  4717.2   0.035       0  4866.4    0.07       0
  4977.7    0.07       0  4981.7    0.07       0
Bank Sta=4977.7,4981.7
Exp/Cntr=0.3,0.1

Type RM Length L Ch R = 1,18646,224,224,224
BEGIN DESCRIPTION:
Elm 01 32 18646.07
END DESCRIPTION:
XS GIS Cut Line= 3
      1542454.98      6832199.37      1541997.96      6831590.02
      1541486.24      6831132.98
#Sta/Elev= 30
  4241.2 1838.24  4347.7 1836.92  4499.3 1834.36  4556.7 1834.12  4620.2 1833.81
  4649.3 1831.70  4690.9 1831.14  4699.3 1831.87  4713.9 1830.46  4742.9 1830.81
  4801.1 1829.72  4834.7 1830.02  4855.6 1829.12  4899.3 1829.97  4907.3 1829.22
  4920.2 1829.51  4963.9 1828.23  4978.5 1829.40  5013.5 1828.33  5027.7 1828.84
  5032.4 1828.17  5032.7 1827.67  5036.4 1828.17  5041.9 1829.12  5070.3 1828.87
  5148.1 1830.46  5154.8 1830.02  5162.3 1830.78  5261.6 1830.75  5689.0 1834.57
#Mann=8,-1,0
  4241.2   0.035       0  4347.7   0.045       0  4556.7   0.035       0
  4690.9    0.07       0  4801.1   0.035       0  4907.3    0.07       0
  5032.4    0.07       0  5036.4    0.07       0
Bank Sta=5032.4,5036.4
Exp/Cntr=0.3,0.1

Type RM Length L Ch R = 1,18422,426,426,426
BEGIN DESCRIPTION:
Elm 01 32 18421.7
END DESCRIPTION:
XS GIS Cut Line= 3
      1542537.02      6832148.61      1542181.56      6831484.55
      1542052.99      6830791.08
#Sta/Elev= 30
  4250.9 1836.75  4297.0 1835.57  4319.6 1836.03  4349.3 1835.09  4457.2 1834.17
  4475.2 1834.24  4519.1 1832.19  4546.6 1831.89  4595.5 1830.98  4659.9 1829.99
  4708.2 1828.29  4745.9 1827.06  4754.7 1827.43  4769.0 1825.67  4769.2 1825.17
  4773.1 1825.67  4792.9 1826.60  4821.0 1826.26  4852.7 1826.97  4894.5 1826.50
  4946.5 1827.47  4968.4 1827.14  4977.5 1825.78  5009.2 1827.28  5183.7 1829.67
  5251.8 1829.66  5399.5 1831.55  5478.6 1831.45  5549.8 1832.63  5709.4 1833.44
#Mann=11,-1,0
  4250.9   0.035       0  4457.2    0.07       0  4546.6   0.035       0
  4595.5    0.07       0  4708.2   0.035       0  4745.9    0.07       0
  4769.0    0.07       0  4773.1    0.07       0  4821.0   0.035       0
  4894.5    0.07       0  5251.8   0.035       0
Bank Sta=4769,4773.1
Exp/Cntr=0.3,0.1

Type RM Length L Ch R = 1,17996,397,397,397
BEGIN DESCRIPTION:
Elm 01 32 17996.16
END DESCRIPTION:
XS GIS Cut Line= 3
      1542615.15      6832281.42      1542568.28      6831449.39
      1542415.94      6830664.28
#Sta/Elev= 30
  4154.5 1838.88  4228.0 1838.05  4318.2 1835.78  4388.3 1834.89  4408.3 1835.31
  4488.4 1831.63  4600.1 1828.63  4618.7 1828.49  4628.7 1827.09  4686.7 1824.60
  4687.0 1824.10  4690.6 1824.10  4690.9 1824.60  4737.0 1825.94  4776.7 1825.40
  4839.0 1826.05  4889.1 1825.16  4969.2 1825.93  4979.2 1825.34  4986.0 1826.29
  5019.8 1826.18  5056.4 1827.07  5111.5 1828.32  5162.4 1827.94  5284.7 1828.71
  5335.6 1828.45  5569.9 1831.28  5672.7 1831.21  5753.3 1833.13  5787.6 1832.72
#Mann=7,-1,0
  4154.5    0.07       0  4600.1   0.035       0  4686.7    0.07       0
  4690.9   0.035       0  4737.0    0.07       0  5056.4   0.035       0
  5672.7    0.07       0
Bank Sta=4686.7,4690.9
Exp/Cntr=0.3,0.1

Type RM Length L Ch R = 1,17599,273,273,273
BEGIN DESCRIPTION:
Elm 01 32 17599.37
END DESCRIPTION:
XS GIS Cut Line= 3
      1542884.68      6832359.50      1542884.68      6831640.80
      1542814.41      6830762.41
#Sta/Elev= 30
  4277.9 1837.98  4299.4 1838.09  4339.4 1836.88  4409.4 1835.87  4419.4 1835.22
  4489.4 1834.26  4659.4 1829.55  4701.2 1827.54  4739.4 1825.37  4757.3 1823.37
  4757.6 1822.87  4761.2 1822.87  4761.5 1823.37  4779.4 1824.52  4969.4 1825.11
  4979.4 1824.99  4989.4 1823.39  5000.5 1823.53  5009.4 1825.04  5103.7 1825.44
  5240.2 1826.48  5305.7 1826.39  5340.5 1827.23  5485.7 1826.87  5611.4 1827.36
  5651.5 1827.83  5679.4 1829.09  5711.7 1828.71  5791.9 1829.26  5877.8 1831.84
#Mann=6,-1,0
  4277.9    0.07       0  4701.2   0.035       0  4757.3   0.035       0
  4761.5   0.035       0  5103.7    0.07       0  5485.7   0.035       0
Bank Sta=4757.3,4761.5
Exp/Cntr=0.3,0.1

Type RM Length L Ch R = 1,17326,255,255,255
BEGIN DESCRIPTION:
Elm 01 32 5.0
END DESCRIPTION:
XS GIS Cut Line= 3
      1543062.79      6832361.30      1543103.08      6831573.01
      1542974.77      6830662.33
#Sta/Elev= 30
  4183.2 1835.49  4406.8 1831.65  4416.8 1831.03  4516.1 1829.12  4607.1 1826.60
  4637.1 1825.25  4667.1 1829.08  4714.2 1829.47  4719.2 1828.53  4727.2 1828.50
  4777.3 1830.24  4797.3 1829.69  4847.4 1830.38  4907.3 1827.45  4917.5 1824.53
  4927.5 1824.06  5048.3 1824.09  5059.4 1823.40  5076.4 1823.27  5076.7 1822.77
  5080.5 1822.77  5080.8 1823.27  5212.3 1825.08  5243.2 1824.70  5634.0 1827.04
  5765.3 1828.94  5775.4 1828.69  5781.7 1829.01  5786.8 1830.06  5892.2 1831.38
#Mann=5,-1,0
  4183.2    0.07       0  5059.4   0.035       0  5076.4    0.07       0
  5080.8   0.035       0  5243.2    0.07       0
Bank Sta=5076.4,5080.8
Exp/Cntr=0.3,0.1

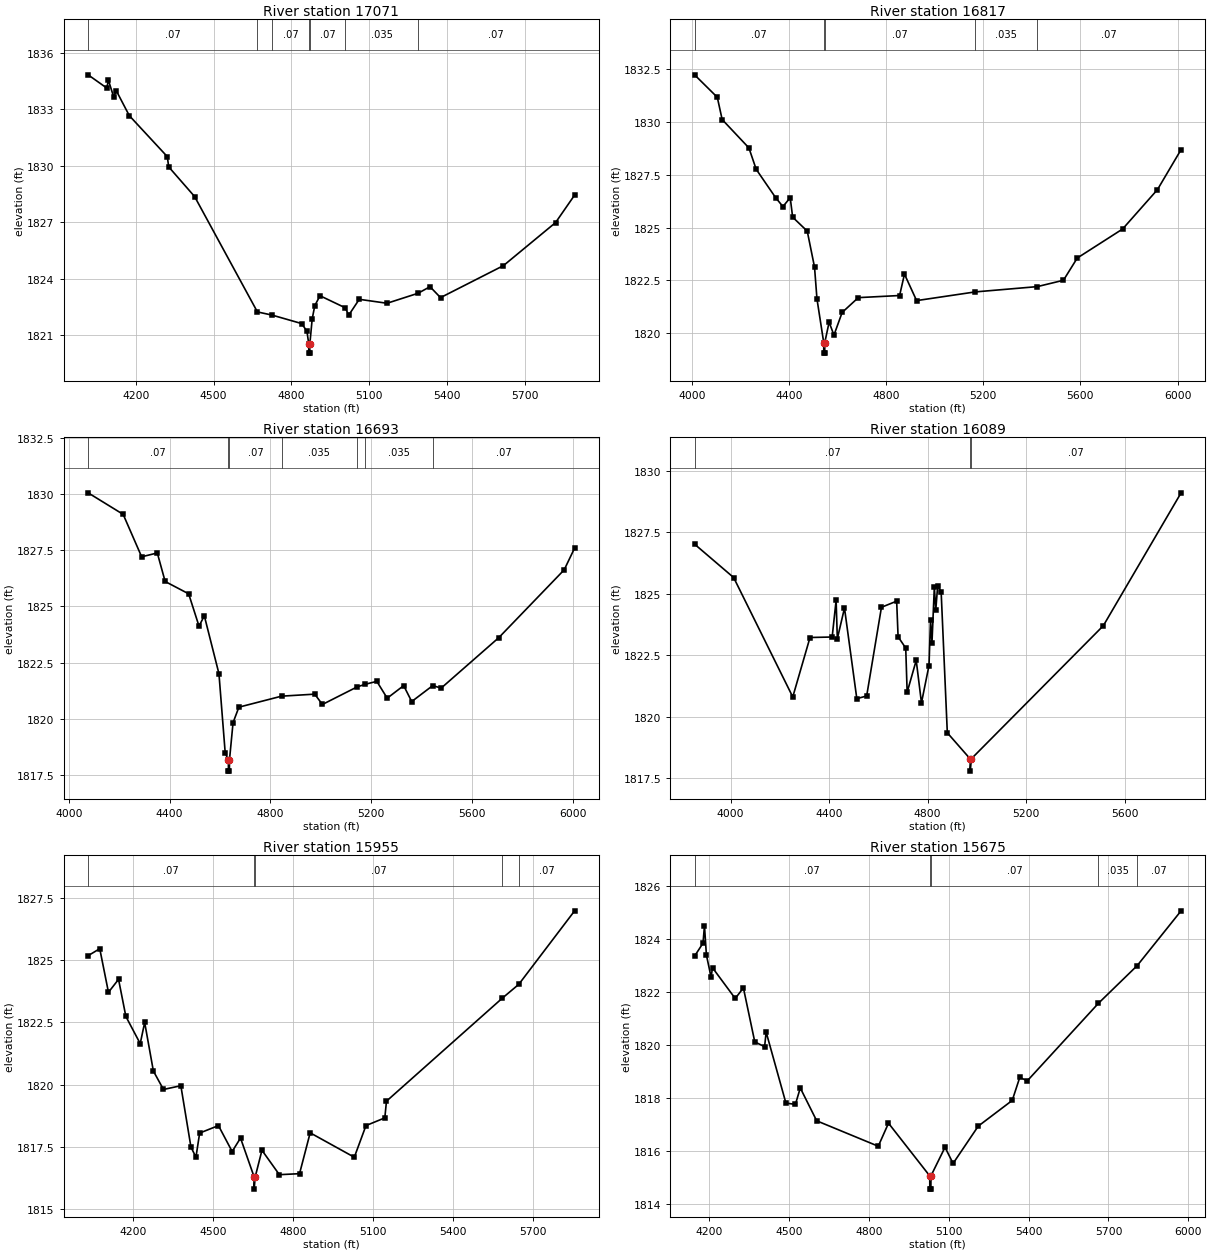
Type RM Length L Ch R = 1,17071,254,254,254
BEGIN DESCRIPTION:
Elm 01 32 17070.82
END DESCRIPTION:
XS GIS Cut Line= 3
      1543201.09      6832515.76      1543326.09      6831539.24
      1543189.37      6830656.45
#Sta/Elev= 30
  4015.4 1834.83  4087.2 1834.13  4093.8 1834.54  4114.0 1833.66  4124.0 1833.99
  4174.4 1832.66  4321.2 1830.48  4326.3 1829.94  4426.5 1828.36  4668.8 1822.23
  4725.7 1822.06  4839.8 1821.61  4860.0 1821.20  4866.9 1820.54  4867.2 1820.04
  4871.0 1820.04  4871.3 1820.54  4880.2 1821.85  4890.2 1822.56  4910.4 1823.09
  5007.7 1822.45  5021.4 1822.06  5061.9 1822.90  5169.2 1822.69  5288.6 1823.22
  5335.1 1823.57  5375.6 1822.99  5618.4 1824.69  5819.8 1826.98  5893.2 1828.44
#Mann=7,-1,0
  4015.4    0.07       0  4668.8   0.035       0  4725.7    0.07       0
  4866.9    0.07       0  4871.3    0.07       0  5007.7   0.035       0
  5288.6    0.07       0
Bank Sta=4866.9,4871.3
Exp/Cntr=0.3,0.1

Type RM Length L Ch R = 1,16817,124,124,124
BEGIN DESCRIPTION:
Elm 01 32 16816.87
END DESCRIPTION:
XS GIS Cut Line= 3
      1543591.71      6832531.46      1543556.56      6831550.96
      1543220.61      6830586.10
#Sta/Elev= 30
  4011.6 1832.21  4105.1 1831.15  4125.1 1830.10  4235.2 1828.76  4265.2 1827.75
  4345.3 1826.41  4375.3 1825.99  4405.3 1826.41  4415.3 1825.49  4475.4 1824.83
  4505.4 1823.13  4515.4 1821.63  4543.2 1819.57  4543.5 1819.07  4547.3 1819.07
  4547.6 1819.57  4565.4 1820.53  4585.4 1819.92  4619.0 1820.99  4685.5 1821.69
  4855.6 1821.79  4875.6 1822.80  4925.6 1821.55  5166.7 1821.96  5422.3 1822.21
  5530.1 1822.51  5587.0 1823.56  5773.6 1824.93  5917.1 1826.79  6014.4 1828.68
#Mann=5,-1,0
  4011.6    0.07       0  4543.2    0.07       0  4547.6    0.07       0
  5166.7   0.035       0  5422.3    0.07       0
Bank Sta=4543.2,4547.6
Exp/Cntr=0.3,0.1

Type RM Length L Ch R = 1,16693,604,604,604
BEGIN DESCRIPTION:
Elm 01 32 16692.91
END DESCRIPTION:
XS GIS Cut Line= 3
      1543908.11      6832382.96      1543662.03      6831488.46
      1543279.61      6830559.74
#Sta/Elev= 30
  4076.2 1830.06  4215.4 1829.10  4288.8 1827.21  4351.0 1827.38  4382.1 1826.11
  4475.5 1825.56  4516.6 1824.12  4537.7 1824.58  4595.8 1822.00  4620.7 1818.46
  4633.2 1818.16  4633.5 1817.66  4637.3 1817.66  4637.6 1818.16  4651.8 1819.82
  4675.0 1820.51  4844.5 1821.00  4976.2 1821.09  5006.6 1820.63  5144.0 1821.41
  5176.7 1821.53  5222.7 1821.66  5264.0 1820.91  5329.4 1821.47  5361.3 1820.76
  5444.7 1821.47  5478.4 1821.36  5707.4 1823.61  5966.9 1826.63  6008.3 1827.60
#Mann=7,-1,0
  4076.2    0.07       0  4633.2   0.035       0  4637.6    0.07       0
  4844.5   0.035       0  5144.0    0.07       0  5176.7   0.035       0
  5444.7    0.07       0
Bank Sta=4633.2,4637.6
Exp/Cntr=0.3,0.1

Type RM Length L Ch R = 1,16089,134,134,134
BEGIN DESCRIPTION:
Elm 01 32 3.0
END DESCRIPTION:
XS GIS Cut Line= 5
      1543961.21      6832146.63      1543945.76      6831353.08
      1543839.16      6831178.28      1543763.26      6830949.64
      1543306.73      6830372.02
#Sta/Elev= 30
  3853.5 1827.02  4012.2 1825.66  4252.2 1820.80  4322.2 1823.22  4412.2 1823.24
  4428.2 1824.73  4433.2 1823.17  4462.2 1824.42  4512.3 1820.73  4552.3 1820.84
  4612.3 1824.45  4674.1 1824.70  4679.9 1823.25  4710.9 1822.79  4716.7 1820.99
  4753.5 1822.29  4774.8 1820.56  4805.4 1822.08  4811.6 1823.93  4817.4 1822.99
  4827.1 1825.27  4832.9 1824.33  4840.6 1825.32  4854.7 1825.09  4879.8 1819.34
  4972.5 1818.28  4972.9 1817.78  4977.1 1818.28  5513.3 1823.70  5829.1 1829.11
#Mann=3,-1,0
  3853.5    0.07       0  4972.5    0.07       0  4977.1    0.07       0
Bank Sta=4972.5,4977.1
Exp/Cntr=0.3,0.1

Type RM Length L Ch R = 1,15955,280,280,280
BEGIN DESCRIPTION:
Elm 01 32 15954.66
END DESCRIPTION:
XS GIS Cut Line= 3
      1544212.81      6831965.02      1543927.65      6831039.24
      1543412.49      6830352.36
#Sta/Elev= 30
  4030.1 1825.18  4073.8 1825.46  4106.5 1823.71  4144.4 1824.23  4171.9 1822.74
  4225.8 1821.65  4242.5 1822.50  4275.2 1820.55  4313.1 1819.81  4378.4 1819.96
  4416.3 1817.50  4435.1 1817.09  4449.0 1818.06  4519.6 1818.36  4571.1 1817.32
  4602.5 1817.86  4653.3 1816.31  4653.6 1815.81  4657.9 1816.31  4683.0 1817.37
  4748.4 1816.39  4824.2 1816.43  4864.1 1818.07  5029.9 1817.09  5073.7 1818.36
  5144.5 1818.67  5150.7 1819.34  5585.3 1823.47  5647.7 1824.03  5857.4 1826.98
#Mann=5,-1,0
  4030.1    0.07       0  4653.3    0.07       0  4657.9    0.07       0
  5585.3   0.035       0  5647.7    0.07       0
Bank Sta=4653.3,4657.9
Exp/Cntr=0.3,0.1

Type RM Length L Ch R = 1,15675,389,389,389
BEGIN DESCRIPTION:
Elm 01 32 15674.67
END DESCRIPTION:
XS GIS Cut Line= 3
      1544482.34      6831859.55      1544126.87      6830914.24
      1543569.16      6830317.53
#Sta/Elev= 30
  4145.9 1823.36  4177.6 1823.85  4183.0 1824.51  4190.3 1823.40  4207.8 1822.57
  4213.2 1822.92  4298.5 1821.76  4329.2 1822.16  4371.9 1820.12  4408.8 1819.94
  4414.6 1820.49  4488.8 1817.81  4524.4 1817.76  4542.8 1818.38  4604.4 1817.14
  4835.5 1816.18  4874.0 1817.05  5028.8 1815.06  5029.2 1814.56  5033.1 1814.56
  5033.4 1815.06  5086.2 1816.14  5116.5 1815.53  5211.1 1816.94  5338.6 1817.91
  5366.9 1818.78  5395.2 1818.65  5662.4 1821.58  5807.7 1823.00  5972.6 1825.07
#Mann=5,-1,0
  4145.9    0.07       0  5028.8    0.07       0  5033.4    0.07       0
  5662.4   0.035       0  5807.7    0.07       0
Bank Sta=5028.8,5033.4
Exp/Cntr=0.3,0.1

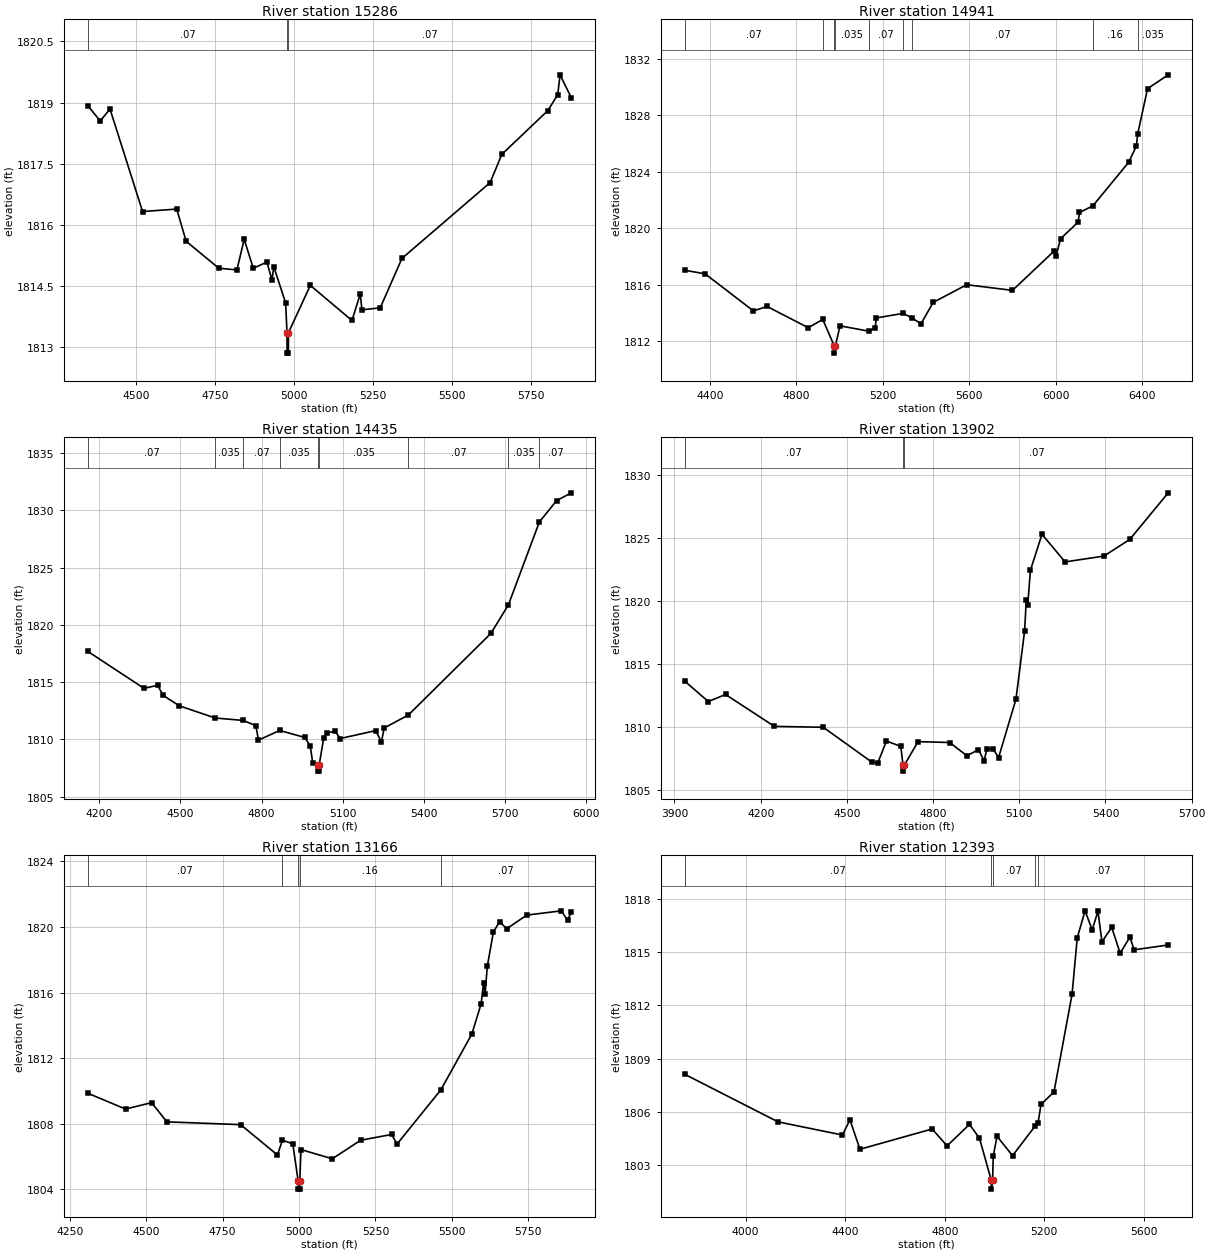
Type RM Length L Ch R = 1,15286,345,345,345
BEGIN DESCRIPTION:
Elm 01 32 15287
END DESCRIPTION:
XS GIS Cut Line= 3
      1544837.83      6831558.80      1544517.49      6830992.36
      1544239.46      6830157.17
#Sta/Elev= 30
  4347.1 1818.92  4385.8 1818.55  4417.0 1818.84  4520.1 1816.33  4628.3 1816.39
  4658.2 1815.60  4761.6 1814.94  4819.0 1814.90  4842.0 1815.65  4870.8 1814.94
  4914.1 1815.09  4930.0 1814.65  4935.7 1814.98  4973.3 1814.09  4977.6 1813.36
  4977.9 1812.86  4981.9 1812.86  4982.2 1813.36  5051.5 1814.52  5183.4 1813.66
  5209.7 1814.31  5215.0 1813.92  5273.0 1813.97  5341.6 1815.18  5621.1 1817.04
  5658.0 1817.73  5803.4 1818.80  5835.1 1819.19  5842.5 1819.68  5878.1 1819.12
#Mann=3,-1,0
  4347.1    0.07       0  4977.6    0.07       0  4982.2    0.07       0
Bank Sta=4977.6,4982.2
Exp/Cntr=0.3,0.1

Type RM Length L Ch R = 1,14941,506,506,506
BEGIN DESCRIPTION:
Elm 01 32 14941.39
END DESCRIPTION:
XS GIS Cut Line= 3
      1545033.11      6831476.71      1544790.93      6830797.05
      1544501.87      6829308.78
#Sta/Elev= 30
  4283.2 1817.02  4377.0 1816.77  4600.3 1814.15  4664.0 1814.46  4854.2 1812.96
  4921.7 1813.54  4975.1 1811.66  4975.4 1811.16  4979.8 1811.66  5001.6 1813.09
  5135.5 1812.71  5164.3 1812.96  5169.4 1813.65  5293.0 1813.97  5334.1 1813.66
  5376.2 1813.23  5432.9 1814.75  5588.0 1816.00  5799.9 1815.60  5991.9 1818.37
  6001.6 1818.02  6022.4 1819.25  6103.9 1820.43  6110.0 1821.11  6172.1 1821.58
  6338.2 1824.67  6373.6 1825.82  6379.6 1826.67  6425.3 1829.87  6520.8 1830.85
#Mann=9,-1,0
  4283.2    0.07       0  4921.7   0.035       0  4975.1   0.035       0
  4979.8   0.035       0  5135.5    0.07       0  5293.0   0.035       0
  5334.1    0.07       0  6172.1    0.16       0  6379.6   0.035       0
Bank Sta=4975.1,4979.8
Exp/Cntr=0.3,0.1

Type RM Length L Ch R = 1,14435,533,533,533
BEGIN DESCRIPTION:
Elm 01 32 14435.24
END DESCRIPTION:
XS GIS Cut Line= 3
      1545154.22      6831523.59      1545263.59      6830695.49
      1545412.02      6829754.11
#Sta/Elev= 30
  4157.7 1817.68  4365.1 1814.46  4415.5 1814.73  4435.9 1813.84  4496.2 1812.93
  4628.7 1811.87  4731.5 1811.66  4778.6 1811.21  4788.7 1809.94  4867.1 1810.78
  4960.2 1810.17  4980.4 1809.41  4989.2 1807.96  5008.3 1807.73  5008.7 1807.23
  5012.7 1807.23  5013.0 1807.73  5030.0 1810.13  5041.1 1810.56  5071.4 1810.71
  5091.7 1810.08  5222.5 1810.77  5243.5 1809.77  5253.7 1811.00  5343.1 1812.13
  5648.5 1819.26  5713.3 1821.75  5828.0 1829.00  5891.4 1830.85  5946.0 1831.54
#Mann=9,-1,0
  4157.7    0.07       0  4628.7   0.035       0  4731.5    0.07       0
  4867.1   0.035       0  5008.3   0.035       0  5013.0   0.035       0
  5343.1    0.07       0  5713.3   0.035       0  5828.0    0.07       0
Bank Sta=5008.3,5013
Exp/Cntr=0.3,0.1

Type RM Length L Ch R = 1,13902,736,736,736
BEGIN DESCRIPTION:
Elm 01 32 13901.66
END DESCRIPTION:
XS GIS Cut Line= 3
      1545712.81      6831609.60      1545704.99      6830554.86
      1545775.13      6829931.46
#Sta/Elev= 30
  3936.2 1813.64  4017.8 1812.03  4077.8 1812.59  4247.8 1810.06  4417.8 1809.99
  4587.8 1807.21  4607.8 1807.17  4637.8 1808.90  4687.8 1808.47  4695.2 1807.01
  4695.6 1806.51  4700.5 1807.01  4747.8 1808.85  4857.8 1808.78  4917.8 1807.73
  4957.8 1808.21  4977.8 1807.33  4986.9 1808.24  5007.9 1808.30  5028.1 1807.59
  5088.4 1812.21  5118.6 1817.63  5124.4 1820.10  5129.5 1819.72  5138.8 1822.44
  5179.0 1825.30  5259.5 1823.11  5394.4 1823.57  5484.5 1824.89  5618.3 1828.59
#Mann=3,-1,0
  3936.2    0.07       0  4695.2    0.07       0  4700.5    0.07       0
Bank Sta=4695.2,4700.5
Exp/Cntr=0.3,0.1

Type RM Length L Ch R = 1,13166,773,773,773
BEGIN DESCRIPTION:
Elm 01 32 13166.33
END DESCRIPTION:
XS GIS Cut Line= 3
      1546091.71      6831625.13      1546025.31      6830929.86
      1546150.15      6830055.97
#Sta/Elev= 30
  4309.6 1809.86  4432.5 1808.90  4517.7 1809.29  4567.9 1808.12  4809.0 1807.95
  4929.5 1806.10  4945.8 1807.00  4979.8 1806.78  4997.2 1804.52  4997.6 1804.02
  5002.1 1804.02  5002.6 1804.52  5006.5 1806.43  5108.9 1805.87  5201.8 1807.00
  5302.9 1807.35  5321.0 1806.77  5464.1 1810.07  5565.5 1813.47  5595.8 1815.31
  5603.9 1816.58  5608.9 1815.94  5616.0 1817.59  5636.2 1819.71  5656.4 1820.31
  5679.6 1819.89  5745.3 1820.72  5858.4 1820.98  5878.6 1820.40  5890.8 1820.91
#Mann=5,-1,0
  4309.6    0.07       0  4945.8    0.16       0  4997.2    0.07       0
  5002.6    0.16       0  5464.1    0.07       0
Bank Sta=4997.2,5002.6
Exp/Cntr=0.3,0.1

Type RM Length L Ch R = 1,12393,670,670,670
BEGIN DESCRIPTION:
Elm 01 32 12393.45
END DESCRIPTION:
XS GIS Cut Line= 3
      1546591.88      6831980.97      1546619.06      6830742.36
      1546427.64      6830066.56
#Sta/Elev= 30
  3756.4 1808.12  4130.6 1805.45  4389.5 1804.71  4419.5 1805.57  4459.5 1803.91
  4749.6 1805.05  4809.6 1804.10  4899.6 1805.31  4939.7 1804.53  4987.0 1802.17
  4987.4 1801.67  4992.4 1802.17  4995.0 1803.52  5010.2 1804.64  5072.6 1803.55
  5164.6 1805.24  5174.7 1805.37  5186.9 1806.43  5238.9 1807.13  5311.6 1812.62
  5332.4 1815.79  5363.8 1817.31  5392.5 1816.24  5415.6 1817.29  5431.7 1815.57
  5470.8 1816.38  5504.8 1814.93  5543.9 1815.83  5561.1 1815.12  5697.7 1815.39
#Mann=5,-1,0
  3756.4    0.07       0  4987.0    0.07       0  4992.4    0.07       0
  5164.6    0.16       0  5174.7    0.07       0
Bank Sta=4987,4992.4
Exp/Cntr=0.3,0.1

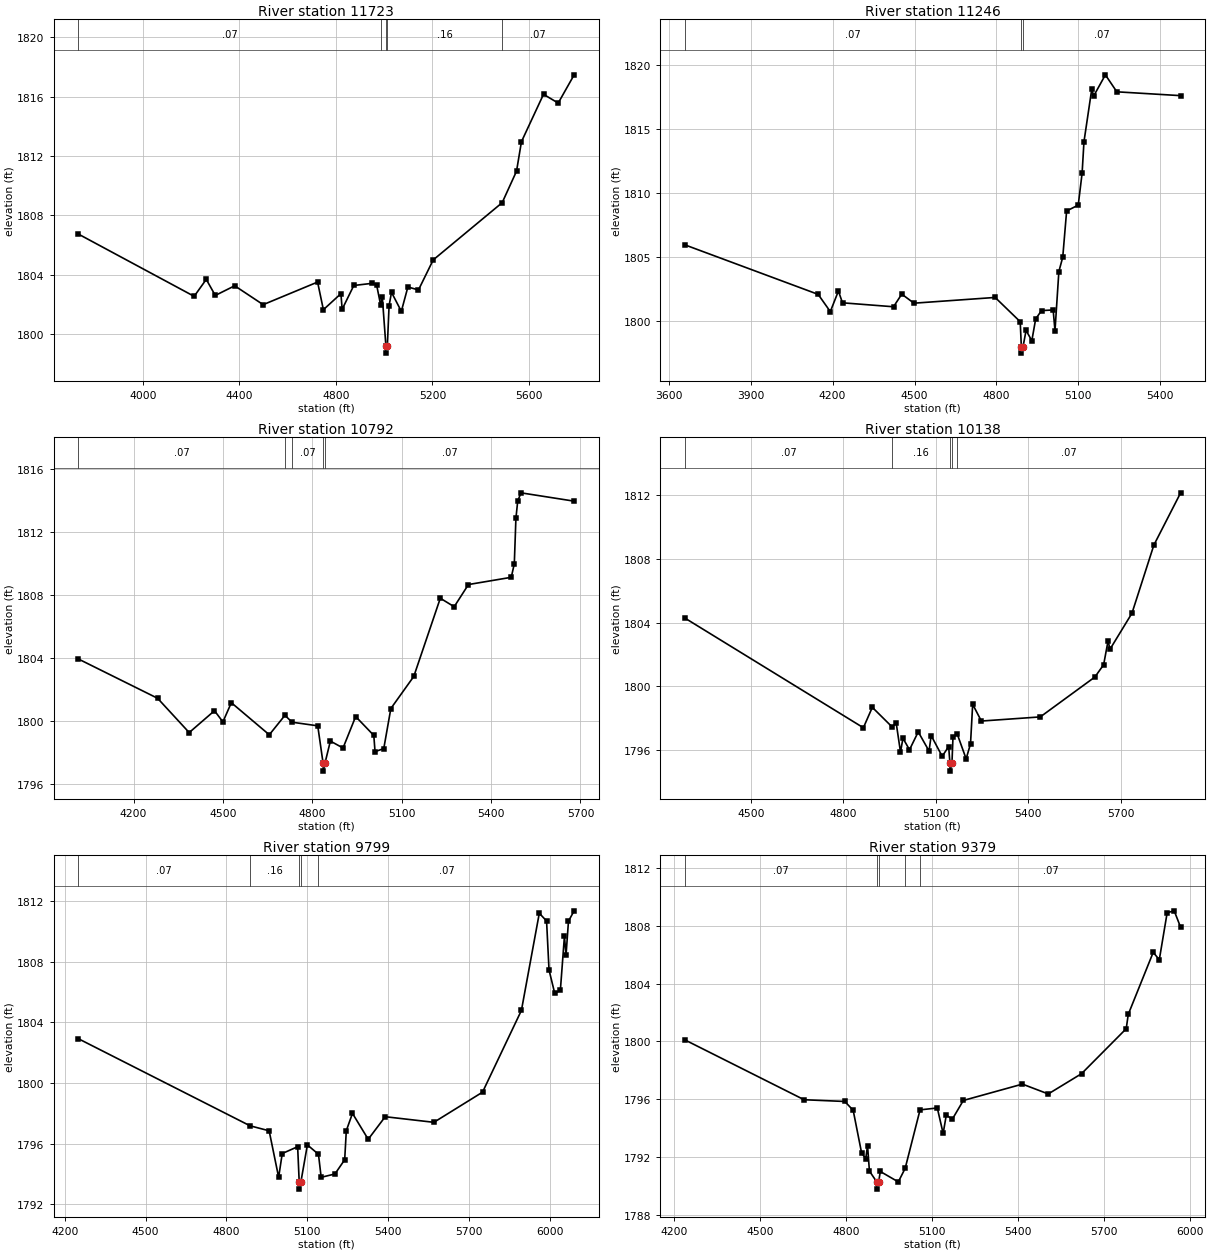
Type RM Length L Ch R = 1,11723,477,477,477
BEGIN DESCRIPTION:
Elm 01 32 11721.69
END DESCRIPTION:
XS GIS Cut Line= 3
      1546778.08      6831895.07      1547162.03      6830691.58
      1547299.14      6829912.91
#Sta/Elev= 30
  3733.0 1806.75  4212.8 1802.56  4262.9 1803.70  4300.3 1802.62  4380.7 1803.27
  4498.7 1802.00  4724.1 1803.52  4748.1 1801.66  4820.7 1802.74  4825.9 1801.69
  4874.1 1803.29  4947.5 1803.43  4968.5 1803.34  4985.2 1801.98  4992.2 1802.51
  5007.0 1799.24  5007.5 1798.74  5013.1 1799.24  5020.2 1801.93  5030.3 1802.83
  5071.0 1801.55  5098.1 1803.19  5142.0 1802.99  5203.0 1805.01  5488.7 1808.86
  5548.2 1810.98  5568.5 1812.96  5659.9 1816.15  5720.8 1815.56  5786.9 1817.46
#Mann=5,-1,0
  3733.0    0.07       0  4985.2    0.16       0  5007.0    0.07       0
  5013.1    0.16       0  5488.7    0.07       0
Bank Sta=5007,5013.1
Exp/Cntr=0.3,0.1

Type RM Length L Ch R = 1,11246,454,454,454
BEGIN DESCRIPTION:
Elm 01 32 11246.48
END DESCRIPTION:
XS GIS Cut Line= 4
      1546869.70      6831929.60      1547321.59      6831038.58
      1547568.28      6830800.96      1547918.52      6830481.84
#Sta/Elev= 30
  3658.9 1805.94  4147.2 1802.06  4191.7 1800.71  4221.3 1802.32  4236.3 1801.40
  4423.1 1801.09  4453.3 1802.08  4497.9 1801.37  4795.2 1801.82  4887.0 1799.92
  4891.1 1797.96  4891.6 1797.46  4897.3 1797.96  4908.4 1799.24  4929.5 1798.43
  4943.6 1800.14  4965.0 1800.79  5007.6 1800.84  5014.3 1799.21  5028.5 1803.85
  5042.7 1804.97  5056.9 1808.59  5099.4 1809.05  5113.6 1811.55  5120.4 1814.01
  5148.8 1818.11  5156.2 1817.60  5198.8 1819.25  5240.7 1817.92  5474.3 1817.62
#Mann=3,-1,0
  3658.9    0.07       0  4891.1    0.07       0  4897.3    0.07       0
Bank Sta=4891.1,4897.3
Exp/Cntr=0.3,0.1

Type RM Length L Ch R = 1,10792,654,654,654
BEGIN DESCRIPTION:
Elm 01 32 10792.2
END DESCRIPTION:
XS GIS Cut Line= 3
      1547021.38      6831820.51      1547708.90      6831105.64
      1548329.99      6830847.83
#Sta/Elev= 30
  4014.6 1803.94  4280.7 1801.44  4386.7 1799.26  4471.6 1800.65  4499.9 1799.94
  4528.2 1801.16  4655.6 1799.12  4708.2 1800.36  4731.7 1799.92  4818.2 1799.69
  4836.2 1797.31  4836.7 1796.81  4842.4 1797.31  4860.6 1798.72  4903.1 1798.28
  4945.5 1800.28  5006.4 1799.08  5010.5 1798.05  5039.8 1798.24  5063.6 1800.79
  5140.6 1802.83  5229.6 1807.80  5276.2 1807.26  5324.0 1808.67  5467.8 1809.13
  5478.0 1809.99  5483.4 1812.88  5489.4 1813.97  5500.3 1814.50  5678.9 1813.97
#Mann=5,-1,0
  4014.6    0.07       0  4708.2    0.16       0  4731.7    0.07       0
  4836.2    0.07       0  4842.4    0.07       0
Bank Sta=4836.2,4842.4
Exp/Cntr=0.3,0.1

Type RM Length L Ch R = 1,10138,339,339,339
BEGIN DESCRIPTION:
Elm 01 32 10138.19
END DESCRIPTION:
XS GIS Cut Line= 3
      1547173.71      6832109.58      1547736.24      6831672.05
      1548337.82      6831007.97
#Sta/Elev= 30
  4285.4 1804.29  4864.8 1797.41  4893.8 1798.69  4958.6 1797.45  4971.1 1797.73
  4985.2 1795.89  4993.3 1796.75  5014.4 1796.03  5042.8 1797.15  5077.9 1795.95
  5084.7 1796.92  5120.5 1795.62  5141.5 1796.23  5145.6 1795.19  5146.1 1794.69
  5152.2 1795.19  5155.6 1796.86  5169.8 1796.99  5198.2 1795.46  5212.4 1796.40
  5219.4 1798.88  5247.6 1797.83  5438.8 1798.09  5615.9 1800.59  5644.3 1801.36
  5658.5 1802.84  5665.2 1802.34  5736.2 1804.59  5807.2 1808.86  5894.1 1812.14
#Mann=5,-1,0
  4285.4    0.07       0  4958.6    0.16       0  5145.6    0.07       0
  5152.2    0.16       0  5169.8    0.07       0
Bank Sta=5145.6,5152.2
Exp/Cntr=0.3,0.1

Type RM Length L Ch R = 1,9799,420,420,420
BEGIN DESCRIPTION:
Elm 01 32 9798.51
END DESCRIPTION:
XS GIS Cut Line= 3
      1547388.60      6832375.17      1547978.43      6831910.33
      1548579.07      6831001.58
#Sta/Elev= 30
  4250.3 1802.93  4887.7 1797.18  4958.5 1796.85  4993.8 1793.78  5007.1 1795.35
  5064.3 1795.80  5070.0 1793.50  5070.5 1793.00  5076.6 1793.50  5100.4 1795.92
  5141.6 1795.30  5151.6 1793.78  5202.7 1794.00  5238.9 1794.94  5244.9 1796.86
  5267.8 1798.00  5326.2 1796.29  5389.3 1797.78  5569.9 1797.41  5750.5 1799.40
  5894.9 1804.80  5961.2 1811.21  5988.2 1810.70  5997.3 1807.47  6018.4 1805.93
  6039.4 1806.12  6054.5 1809.69  6060.5 1808.46  6069.5 1810.69  6090.6 1811.37
#Mann=5,-1,0
  4250.3    0.07       0  4887.7    0.16       0  5070.0    0.07       0
  5076.6    0.16       0  5141.6    0.07       0
Bank Sta=5070,5076.6
Exp/Cntr=0.3,0.1

Type RM Length L Ch R = 1,9379,496,496,496
BEGIN DESCRIPTION:
Elm 01 32 9379.22
END DESCRIPTION:
XS GIS Cut Line= 3
      1547755.81      6832480.62      1548287.03      6832090.02
      1548603.43      6831066.57
#Sta/Elev= 30
  4236.5 1800.11  4652.9 1795.97  4794.9 1795.85  4824.2 1795.24  4853.5 1792.30
  4868.1 1791.89  4874.3 1792.80  4880.9 1791.04  4906.4 1790.29  4906.9 1789.79
  4913.1 1790.29  4918.9 1791.01  4981.7 1790.29  5005.7 1791.23  5057.6 1795.27
  5117.8 1795.40  5138.2 1793.64  5149.2 1794.91  5170.1 1794.62  5208.7 1795.92
  5414.9 1797.05  5505.1 1796.37  5621.2 1797.77  5777.2 1800.88  5784.3 1801.87
  5871.4 1806.16  5892.7 1805.65  5920.1 1808.90  5944.7 1809.03  5967.1 1807.89
#Mann=5,-1,0
  4236.5    0.07       0  4906.4    0.07       0  4913.1    0.07       0
  5005.7    0.16       0  5057.6    0.07       0
Bank Sta=4906.4,4913.1
Exp/Cntr=0.3,0.1

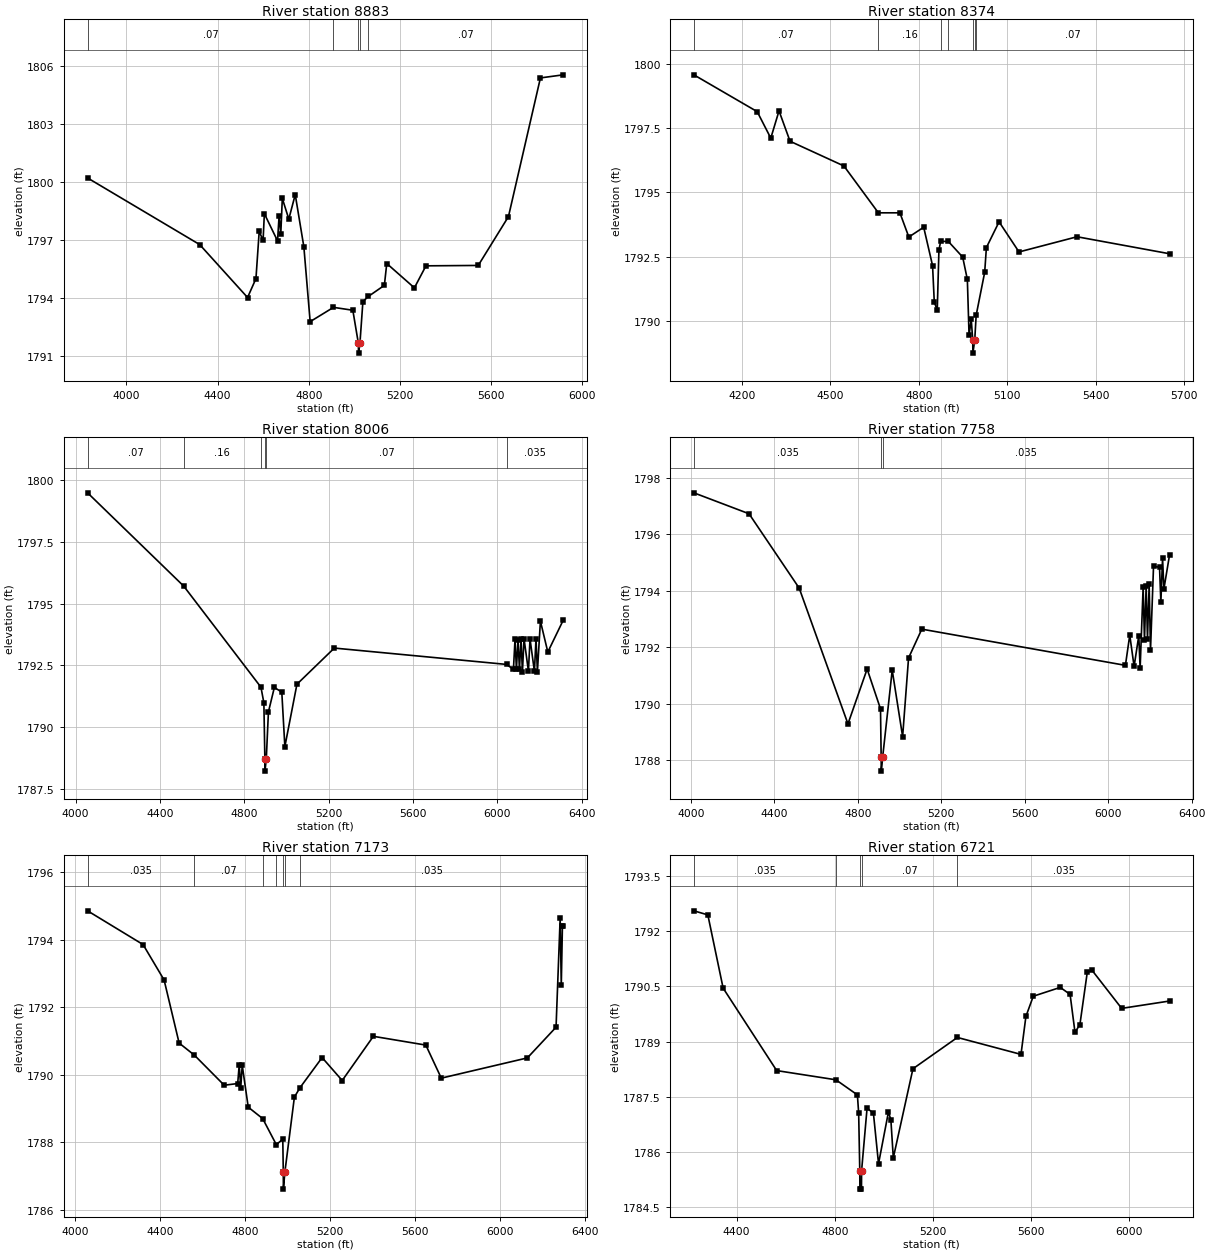
Type RM Length L Ch R = 1,8883,509,509,509
BEGIN DESCRIPTION:
Elm 01 32 9011.32
END DESCRIPTION:
XS GIS Cut Line= 5
      1547767.51      6832625.17      1548474.53      6832289.24
      1548572.18      6832203.30      1548772.02      6831821.41
      1548919.36      6831092.21
#Sta/Elev= 30
  3829.3 1800.21  4321.4 1796.76  4531.5 1794.02  4568.3 1795.00  4582.5 1797.44
  4599.6 1796.98  4605.2 1798.36  4663.1 1796.95  4669.8 1798.24  4677.3 1797.32
  4684.0 1799.15  4712.5 1798.08  4740.7 1799.35  4778.5 1796.65  4806.2 1792.77
  4908.6 1793.51  4993.5 1793.36  5017.9 1791.64  5018.4 1791.14  5024.6 1791.64
  5037.7 1793.81  5062.1 1794.08  5131.9 1794.65  5142.4 1795.78  5263.7 1794.52
  5314.4 1795.66  5543.9 1795.68  5676.5 1798.21  5816.8 1805.39  5917.1 1805.55
#Mann=5,-1,0
  3829.3    0.07       0  4908.6    0.16       0  5017.9    0.07       0
  5024.6    0.16       0  5062.1    0.07       0
Bank Sta=5017.9,5024.6
Exp/Cntr=0.3,0.1

Type RM Length L Ch R = 1,8374,368,368,368
BEGIN DESCRIPTION:
Elm 01 32 8375.48
END DESCRIPTION:
XS GIS Cut Line= 3
      1547888.63      6832836.09      1548720.62      6832359.55
      1549286.10      6832029.60
#Sta/Elev= 30
  4036.9 1799.57  4251.7 1798.14  4297.8 1797.11  4325.7 1798.17  4363.1 1796.99
  4545.8 1796.03  4662.7 1794.21  4735.7 1794.21  4766.0 1793.27  4816.4 1793.65
  4846.5 1792.16  4852.3 1790.75  4862.4 1790.42  4868.1 1792.76  4873.9 1793.10
  4899.9 1793.10  4948.7 1792.49  4964.5 1791.62  4970.3 1789.45  4977.7 1790.07
  4982.8 1789.26  4983.3 1788.76  4989.5 1789.26  4994.4 1790.23  5023.3 1791.90
  5029.1 1792.86  5072.1 1793.86  5139.7 1792.69  5336.5 1793.28  5650.4 1792.62
#Mann=7,-1,0
  4036.9    0.07       0  4662.7    0.16       0  4873.9    0.07       0
  4899.9    0.16       0  4982.8    0.07       0  4989.5    0.16       0
  4994.4    0.07       0
Bank Sta=4982.8,4989.5
Exp/Cntr=0.3,0.1

Type RM Length L Ch R = 1,8006,248,248,248
BEGIN DESCRIPTION:
Elm 01 32 8006.34
END DESCRIPTION:
XS GIS Cut Line= 3
      1547947.16      6833203.32      1548693.28      6832625.18
      1549671.19      6831751.11
#Sta/Elev= 30
  4057.2 1799.47  4513.3 1795.70  4879.2 1791.62  4893.1 1790.99  4897.8 1788.73
  4898.3 1788.23  4904.6 1788.73  4914.7 1790.62  4942.8 1791.61  4978.1 1791.42
  4992.6 1789.22  5049.9 1791.74  5227.1 1793.20  6043.6 1792.54  6076.4 1792.34
  6083.9 1793.55  6090.6 1792.35  6098.1 1793.54  6104.9 1792.35  6112.4 1793.56
  6119.1 1792.24  6126.6 1793.58  6147.5 1792.27  6155.0 1793.57  6175.9 1792.26
  6183.4 1793.58  6190.1 1792.25  6204.3 1794.29  6239.4 1793.04  6312.7 1794.33
#Mann=6,-1,0
  4057.2    0.07       0  4513.3    0.16       0  4879.2    0.07       0
  4897.8    0.07       0  4904.6    0.07       0  6043.6   0.035       0
Bank Sta=4897.8,4904.6
Exp/Cntr=0.3,0.1

Type RM Length L Ch R = 1,7758,585,585,585
BEGIN DESCRIPTION:
Elm 01 32 7661.66
END DESCRIPTION:
XS GIS Cut Line= 3
      1548201.08      6833527.53      1548980.57      6832678.12
      1549677.47      6831792.39
#Sta/Elev= 30
  4014.2 1797.46  4278.5 1796.72  4519.0 1794.09  4752.7 1789.29  4844.6 1791.23
  4908.7 1789.82  4911.8 1788.12  4912.3 1787.62  4919.1 1788.12  4964.8 1791.19
  5014.7 1788.84  5043.1 1791.62  5106.6 1792.64  6082.5 1791.36  6103.3 1792.43
  6124.1 1791.32  6146.6 1792.41  6153.0 1791.25  6167.4 1794.13  6173.8 1792.26
  6181.9 1794.17  6188.3 1792.30  6196.3 1794.22  6202.7 1791.89  6217.2 1794.86
  6246.0 1794.83  6252.4 1793.59  6260.5 1795.15  6266.9 1794.06  6294.1 1795.27
#Mann=3,-1,0
  4014.2   0.035       0  4911.8   0.035       0  4919.1   0.035       0
Bank Sta=4911.8,4919.1
Exp/Cntr=0.3,0.1

Type RM Length L Ch R = 1,7173,452,452,452
BEGIN DESCRIPTION:
Elm 01 32 7172.27
END DESCRIPTION:
XS GIS Cut Line= 3
      1548724.54      6833636.88      1549388.59      6832984.55
      1549742.90      6831725.30
#Sta/Elev= 30
  4058.6 1794.86  4319.8 1793.86  4418.8 1792.81  4489.5 1790.94  4561.6 1790.58
  4701.7 1789.69  4765.2 1789.74  4772.4 1790.30  4779.4 1789.61  4786.5 1790.28
  4814.8 1789.04  4882.9 1788.70  4946.9 1787.93  4977.4 1788.09  4979.8 1787.11
  4980.3 1786.61  4987.1 1787.11  5032.1 1789.34  5058.8 1789.62  5162.5 1790.51
  5257.1 1789.83  5403.7 1791.14  5650.7 1790.88  5723.4 1789.90  6128.6 1790.50
  6263.6 1791.41  6283.0 1794.65  6288.2 1792.65  6293.6 1794.42  6297.6 1794.42
#Mann=7,-1,0
  4058.6   0.035       0  4561.6    0.07       0  4882.9   0.035       0
  4946.9    0.07       0  4979.8    0.07       0  4987.1    0.07       0
  5058.8   0.035       0
Bank Sta=4979.8,4987.1
Exp/Cntr=0.3,0.1

Type RM Length L Ch R = 1,6721,424,424,424
BEGIN DESCRIPTION:
Elm 01 32 6720.87
END DESCRIPTION:
XS GIS Cut Line= 3
      1549540.94      6833972.80      1549744.06      6833242.36
      1549771.40      6832062.83
#Sta/Elev= 30
  4225.8 1792.55  4282.7 1792.44  4345.0 1790.45  4563.2 1788.21  4804.5 1787.96
  4892.0 1787.55  4897.2 1787.05  4901.7 1785.49  4902.2 1784.99  4908.6 1784.99
  4909.1 1785.49  4931.4 1787.19  4957.3 1787.05  4978.1 1785.68  5018.3 1787.08
  5028.3 1786.88  5038.3 1785.84  5118.3 1788.26  5299.3 1789.11  5558.5 1788.65
  5578.5 1789.68  5608.5 1790.23  5718.5 1790.47  5758.5 1790.28  5778.5 1789.25
  5798.5 1789.46  5828.5 1790.88  5848.5 1790.93  5968.6 1789.90  6163.8 1790.10
#Mann=5,-1,0
  4225.8   0.035       0  4804.5    0.07       0  4901.7    0.07       0
  4909.1    0.07       0  5299.3   0.035       0
Bank Sta=4901.7,4909.1
Exp/Cntr=0.3,0.1