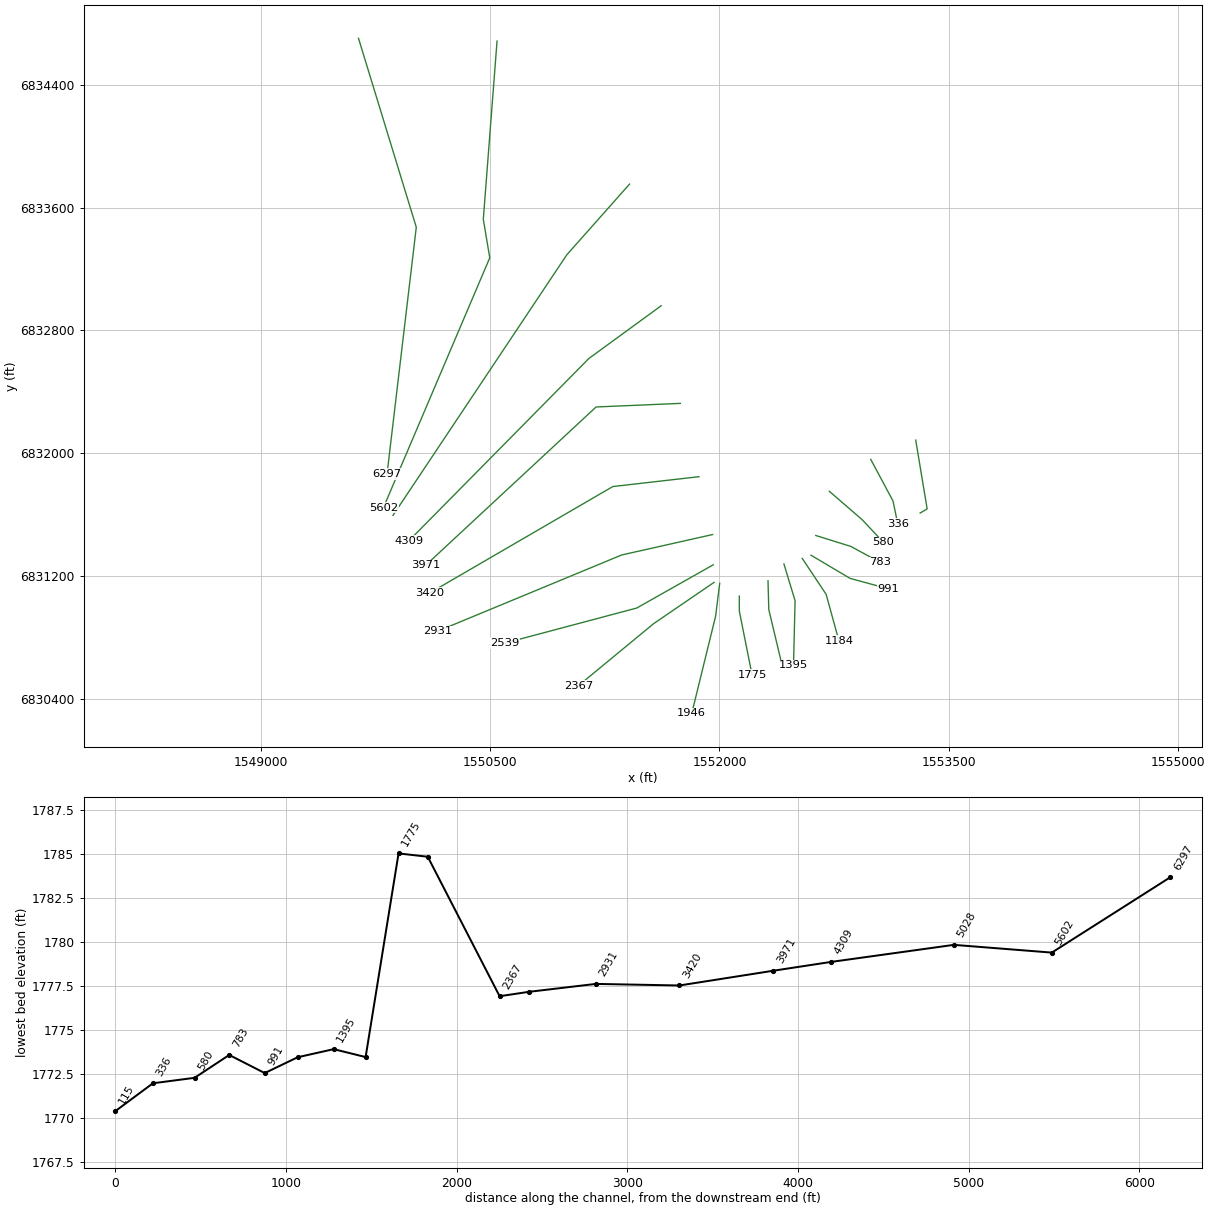
HEC-RAS study Elm 01 32.prj: Elm 01 32 Base Level Engineering

--- Elm 01 32.g01 (geometry) --- (continued)

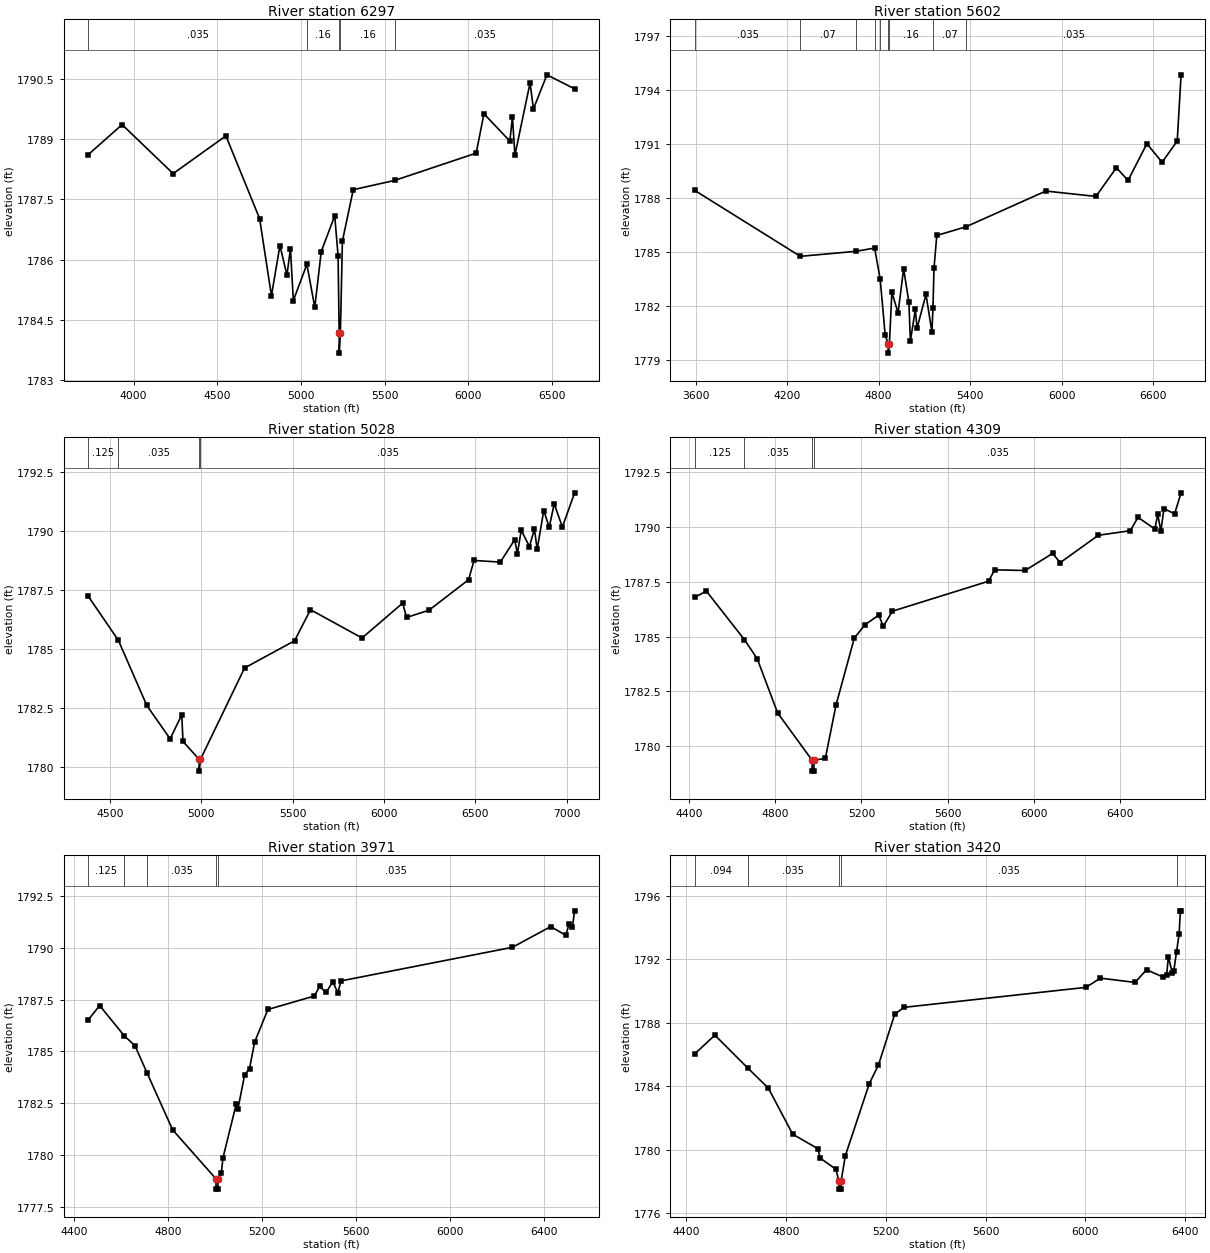
Type RM Length L Ch R = 1,6297,695,695,695
BEGIN DESCRIPTION:
Elm 01 32 6300.34
END DESCRIPTION:
XS GIS Cut Line= 3
      1549639.64      6834704.68      1550017.49      6833472.83
      1549826.09      6831863.47
#Sta/Elev= 30
  3727.6 1788.61  3930.8 1789.36  4235.9 1788.14  4551.5 1789.08  4753.1 1787.02
  4823.8 1785.10  4874.7 1786.35  4916.5 1785.61  4937.5 1786.27  4954.8 1784.98
  5035.7 1785.88  5083.0 1784.81  5121.7 1786.20  5202.2 1787.09  5222.4 1786.09
  5228.7 1784.17  5229.2 1783.67  5236.1 1784.17  5248.2 1786.46  5313.0 1787.74
  5560.1 1787.97  6048.1 1788.65  6094.6 1789.63  6249.6 1788.95  6264.8 1789.55
  6279.8 1788.60  6370.4 1790.40  6390.5 1789.75  6471.1 1790.60  6636.8 1790.25
#Mann=5,-1,0
  3727.6   0.035       0  5035.7    0.16       0  5228.7   0.035       0
  5236.1    0.16       0  5560.1   0.035       0
Bank Sta=5228.7,5236.1
Exp/Cntr=0.3,0.1

Type RM Length L Ch R = 1,5602,574,574,574
BEGIN DESCRIPTION:
Elm 01 32 5601.65
END DESCRIPTION:
XS GIS Cut Line= 4
      1550545.63      6834687.09      1550455.74      6833524.70
      1550497.96      6833273.61      1549802.64      6831644.68
#Sta/Elev= 30
  3592.9 1788.43  4286.8 1784.76  4651.1 1785.04  4774.2 1785.22  4810.7 1783.48
  4843.2 1780.39  4863.2 1779.88  4863.7 1779.38  4870.7 1779.88  4887.2 1782.76
  4927.8 1781.62  4964.3 1784.07  4998.8 1782.21  5008.6 1780.05  5041.2 1781.81
  5052.1 1780.76  5111.0 1782.64  5149.9 1780.55  5156.7 1781.87  5163.6 1784.12
  5181.8 1785.92  5372.2 1786.40  5897.2 1788.39  6225.9 1788.09  6360.2 1789.69
  6436.5 1788.98  6560.0 1791.02  6659.9 1789.99  6759.1 1791.17  6784.5 1794.85
#Mann=9,-1,0
  3592.9   0.035       0  4286.8    0.07       0  4651.1    0.16       0
  4774.2    0.07       0  4810.7    0.16       0  4863.2    0.07       0
  4870.7    0.16       0  5156.7    0.07       0  5372.2   0.035       0
Bank Sta=4863.2,4870.7
Exp/Cntr=0.3,0.1

Type RM Length L Ch R = 1,5028,719,719,719
BEGIN DESCRIPTION:
Elm 01 32 5027.8
END DESCRIPTION:
XS GIS Cut Line= 3
      1551412.01      6833754.06      1551001.87      6833293.14
      1549865.18      6831593.97
#Sta/Elev= 30
  4381.3 1787.25  4546.9 1785.37  4702.1 1782.61  4830.0 1781.19  4893.6 1782.21
  4900.3 1781.08  4988.3 1780.32  4988.8 1779.82  4996.0 1780.32  5237.3 1784.20
  5510.5 1785.35  5597.6 1786.67  5879.8 1785.47  6102.0 1786.95  6123.4 1786.34
  6246.1 1786.65  6462.3 1787.94  6492.4 1788.76  6636.5 1788.69  6714.6 1789.64
  6729.6 1789.05  6750.6 1790.04  6795.6 1789.35  6822.7 1790.10  6837.7 1789.23
  6873.7 1790.88  6903.7 1790.17  6930.8 1791.16  6975.8 1790.18  7042.6 1791.63
#Mann=4,-1,0
  4381.3   0.125       0  4546.9   0.035       0  4988.3   0.035       0
  4996.0   0.035       0
Bank Sta=4988.3,4996
Exp/Cntr=0.3,0.1

Type RM Length L Ch R = 1,4309,338,338,338
BEGIN DESCRIPTION:
Elm 01 32 4308.5
END DESCRIPTION:
XS GIS Cut Line= 3
      1551619.06      6832961.11      1551146.40      6832617.36
      1549970.58      6831429.83
#Sta/Elev= 30
  4426.5 1786.79  4481.0 1787.08  4657.6 1784.86  4717.2 1783.98  4811.5 1781.51
  4971.2 1779.35  4971.7 1778.85  4979.4 1778.85  4979.9 1779.35  5032.7 1779.43
  5082.2 1781.87  5167.0 1784.93  5216.6 1785.54  5280.2 1785.98  5301.4 1785.47
  5343.8 1786.16  5789.3 1787.53  5817.6 1788.05  5959.0 1788.02  6086.3 1788.80
  6121.7 1788.38  6298.4 1789.63  6446.9 1789.84  6482.3 1790.45  6560.0 1789.92
  6574.2 1790.58  6588.3 1789.81  6602.5 1790.85  6652.0 1790.61  6682.1 1791.57
#Mann=4,-1,0
  4426.5   0.125       0  4657.6   0.035       0  4971.2   0.035       0
  4979.9   0.035       0
Bank Sta=4971.2,4979.9
Exp/Cntr=0.3,0.1

Type RM Length L Ch R = 1,3971,551,551,551
BEGIN DESCRIPTION:
Elm 01 32 3970.53
END DESCRIPTION:
XS GIS Cut Line= 3
      1551744.04      6832324.39      1551193.28      6832300.96
      1550079.98      6831269.70
#Sta/Elev= 30
  4460.6 1786.51  4509.7 1787.21  4613.4 1785.76  4659.8 1785.27  4712.3 1783.93
  4820.0 1781.21  5004.1 1778.85  5004.6 1778.35  5012.3 1778.35  5012.8 1778.85
  5026.8 1779.11  5034.1 1779.86  5090.8 1782.47  5097.6 1782.21  5126.0 1783.86
  5147.0 1784.17  5168.5 1785.44  5225.2 1787.02  5423.1 1787.67  5444.6 1788.13
  5473.0 1787.84  5500.8 1788.36  5522.3 1787.83  5536.5 1788.40  6265.0 1790.02
  6427.7 1791.02  6491.8 1790.60  6506.0 1791.15  6520.1 1791.02  6529.4 1791.78
#Mann=5,-1,0
  4460.6   0.125       0  4613.4   0.094       0  4712.3   0.035       0
  5004.1   0.035       0  5012.8   0.035       0
Bank Sta=5004.1,5012.8
Exp/Cntr=0.3,0.1

Type RM Length L Ch R = 1,3420,489,489,489
BEGIN DESCRIPTION:
Elm 01 32 3420.04
END DESCRIPTION:
XS GIS Cut Line= 3
      1551865.86      6831846.41      1551302.73      6831782.06
      1550105.00      6831088.00
#Sta/Elev= 30
  4433.2 1786.02  4514.6 1787.21  4647.0 1785.13  4729.2 1783.87  4826.6 1780.97
  4927.3 1780.06  4937.3 1779.46  5000.0 1778.76  5012.0 1778.01  5012.5 1777.51
  5020.2 1777.51  5020.7 1778.01  5037.9 1779.62  5134.0 1784.16  5170.7 1785.33
  5235.9 1788.53  5273.2 1788.96  6002.9 1790.22  6060.8 1790.80  6200.0 1790.53
  6245.6 1791.33  6311.8 1790.87  6326.5 1791.01  6333.4 1792.15  6349.1 1791.11
  6354.9 1791.25  6365.9 1792.44  6376.4 1793.58  6381.4 1795.04  6384.3 1795.04
#Mann=5,-1,0
  4433.2   0.094       0  4647.0   0.035       0  5012.0   0.035       0
  5020.7   0.035       0  6365.9    0.07       0
Bank Sta=5012,5020.7
Exp/Cntr=0.3,0.1

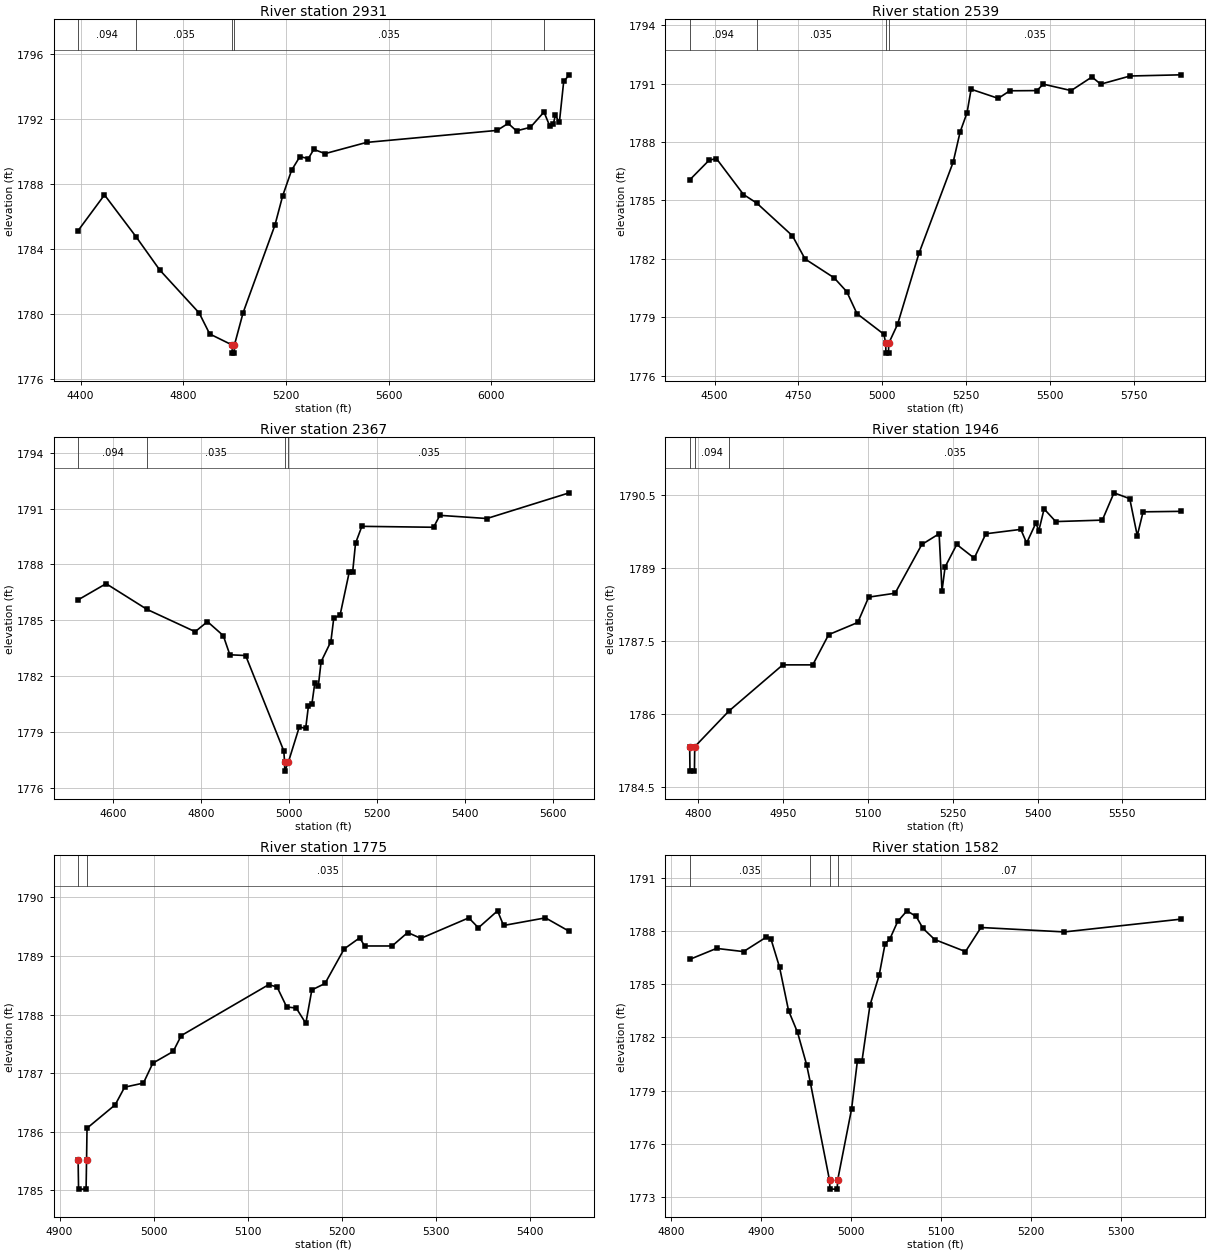
Type RM Length L Ch R = 1,2931,392,392,392
BEGIN DESCRIPTION:
Elm 01 32 2930.844
END DESCRIPTION:
XS GIS Cut Line= 3
      1551955.34      6831469.16      1551360.40      6831335.83
      1550154.96      6830837.98
#Sta/Elev= 30
  4390.3 1785.14  4493.1 1787.34  4615.8 1784.77  4708.3 1782.72  4862.1 1780.07
  4903.1 1778.78  4990.7 1778.10  4991.2 1777.60  4999.0 1777.60  4999.5 1778.10
  5033.3 1780.09  5157.3 1785.48  5187.6 1787.29  5222.3 1788.86  5254.7 1789.70
  5287.1 1789.57  5308.8 1790.14  5352.7 1789.88  5514.3 1790.57  6022.9 1791.31
  6066.1 1791.74  6098.6 1791.28  6152.7 1791.50  6205.7 1792.44  6228.4 1791.57
  6241.7 1791.68  6250.1 1792.24  6265.6 1791.80  6282.5 1794.32  6304.2 1794.73
#Mann=5,-1,0
  4390.3   0.094       0  4615.8   0.035       0  4990.7   0.035       0
  4999.5   0.035       0  6205.7    0.07       0
Bank Sta=4990.7,4999.5
Exp/Cntr=0.3,0.1

Type RM Length L Ch R = 1,2539,172,172,172
BEGIN DESCRIPTION:
Elm 01 32 2538.957
END DESCRIPTION:
XS GIS Cut Line= 3
      1551959.52      6831271.86      1551459.25      6830990.03
      1550598.80      6830761.79
#Sta/Elev= 30
  4425.8 1786.05  4483.6 1787.06  4505.3 1787.15  4586.2 1785.30  4625.7 1784.86
  4732.1 1783.18  4769.7 1781.99  4856.4 1781.02  4894.0 1780.31  4924.5 1779.18
  5004.8 1778.12  5010.3 1777.65  5010.8 1777.15  5018.6 1777.15  5019.1 1777.65
  5045.8 1778.64  5109.2 1782.27  5211.3 1786.96  5232.0 1788.51  5252.7 1789.50
  5264.8 1790.71  5345.8 1790.24  5380.2 1790.63  5460.6 1790.64  5480.3 1790.97
  5563.1 1790.64  5625.1 1791.34  5651.2 1790.97  5738.9 1791.39  5890.2 1791.45
#Mann=4,-1,0
  4425.8   0.094       0  4625.7   0.035       0  5010.3   0.035       0
  5019.1   0.035       0
Bank Sta=5010.3,5019.1
Exp/Cntr=0.3,0.1

Type RM Length L Ch R = 1,2367,421,421,421
BEGIN DESCRIPTION:
Elm 01 32 2367.457
END DESCRIPTION:
XS GIS Cut Line= 3
      1551964.77      6831157.30      1551568.97      6830887.53
      1551076.85      6830482.91
#Sta/Elev= 30
  4521.0 1786.10  4584.6 1786.97  4677.5 1785.59  4787.0 1784.39  4815.0 1784.93
  4850.9 1784.18  4865.8 1783.15  4901.7 1783.11  4988.5 1777.98  4990.1 1777.40
  4990.6 1776.90  4999.0 1777.40  5023.7 1779.28  5038.1 1779.19  5044.5 1780.42
  5052.4 1780.53  5058.9 1781.64  5066.8 1781.46  5073.2 1782.78  5095.4 1783.86
  5101.9 1785.11  5116.3 1785.28  5137.1 1787.59  5145.0 1787.62  5151.4 1789.14
  5165.8 1790.05  5328.8 1790.00  5343.0 1790.64  5449.9 1790.47  5637.1 1791.85
#Mann=4,-1,0
  4521.0   0.094       0  4677.5   0.035       0  4990.1   0.035       0
  4999.0   0.035       0
Bank Sta=4990.1,4999
Exp/Cntr=0.3,0.1

Type RM Length L Ch R = 1,1946,171,171,171
BEGIN DESCRIPTION:
Elm 01 32 1945.637
END DESCRIPTION:
XS GIS Cut Line= 3
      1552001.77      6831151.29      1551975.15      6830937.65
      1551818.92      6830303.10
#Sta/Elev= 30
  4784.7 1785.33  4785.2 1784.83  4793.1 1784.83  4793.6 1785.33  4853.8 1786.06
  4949.3 1787.01  5002.4 1787.01  5030.5 1787.63  5082.0 1787.88  5101.3 1788.40
  5148.0 1788.48  5195.3 1789.48  5225.9 1789.70  5231.0 1788.53  5236.5 1789.02
  5257.1 1789.48  5288.0 1789.20  5308.6 1789.70  5370.4 1789.79  5380.7 1789.51
  5397.1 1789.92  5402.2 1789.76  5411.6 1790.21  5432.2 1789.95  5514.6 1789.98
  5535.2 1790.54  5563.1 1790.42  5576.4 1789.66  5586.7 1790.15  5653.5 1790.16
#Mann=3,-1,0
  4784.7   0.035       0  4793.6   0.094       0  4853.8   0.035       0
Bank Sta=4784.7,4793.6
Exp/Cntr=0.3,0.1

Type RM Length L Ch R = 1,1775,193,193,193
BEGIN DESCRIPTION:
Elm 01 32 1775.002
END DESCRIPTION:
XS GIS Cut Line= 3
      1552129.99      6831067.49      1552130.12      6830969.79
      1552213.45      6830553.14
#Sta/Elev= 30
  4919.7 1785.52  4920.2 1785.02  4928.2 1785.02  4928.7 1785.52  4929.2 1786.06
  4959.2 1786.46  4969.2 1786.76  4989.2 1786.83  4999.2 1787.17  5020.9 1787.37
  5029.4 1787.64  5122.5 1788.51  5131.4 1788.47  5141.6 1788.13  5151.8 1788.11
  5162.0 1787.85  5168.4 1788.42  5182.4 1788.53  5202.8 1789.12  5219.4 1789.31
  5224.5 1789.17  5253.8 1789.17  5270.4 1789.40  5284.4 1789.30  5335.4 1789.65
  5345.6 1789.48  5366.0 1789.77  5372.4 1789.52  5417.0 1789.65  5442.3 1789.42
#Mann=2,-1,0
  4919.7   0.035       0  4928.7   0.035       0
Bank Sta=4919.7,4928.7
Exp/Cntr=0.3,0.1

Type RM Length L Ch R = 1,1582,187,187,187
BEGIN DESCRIPTION:
Elm 01 32 1582.494
END DESCRIPTION:
XS GIS Cut Line= 3
      1552317.62      6831167.74      1552322.83      6830980.21
      1552405.96      6830632.10
#Sta/Elev= 30
  4820.6 1786.40  4850.4 1787.02  4880.4 1786.84  4905.8 1787.66  4910.8 1787.56
  4920.4 1785.96  4930.4 1783.51  4940.4 1782.28  4950.4 1780.47  4954.6 1779.45
  4975.9 1773.94  4976.4 1773.44  4984.4 1773.44  4984.9 1773.94  5000.4 1777.96
  5006.8 1780.65  5011.9 1780.65  5020.8 1783.81  5031.0 1785.50  5037.6 1787.28
  5042.8 1787.54  5051.6 1788.54  5061.9 1789.14  5072.2 1788.82  5079.7 1788.15
  5092.7 1787.52  5126.9 1786.84  5144.1 1788.20  5236.7 1787.95  5366.1 1788.67
#Mann=4,-1,0
  4820.6   0.035       0  4954.6    0.07       0  4975.9    0.07       0
  4984.9    0.07       0
Bank Sta=4975.9,4984.9
Exp/Cntr=0.3,0.1

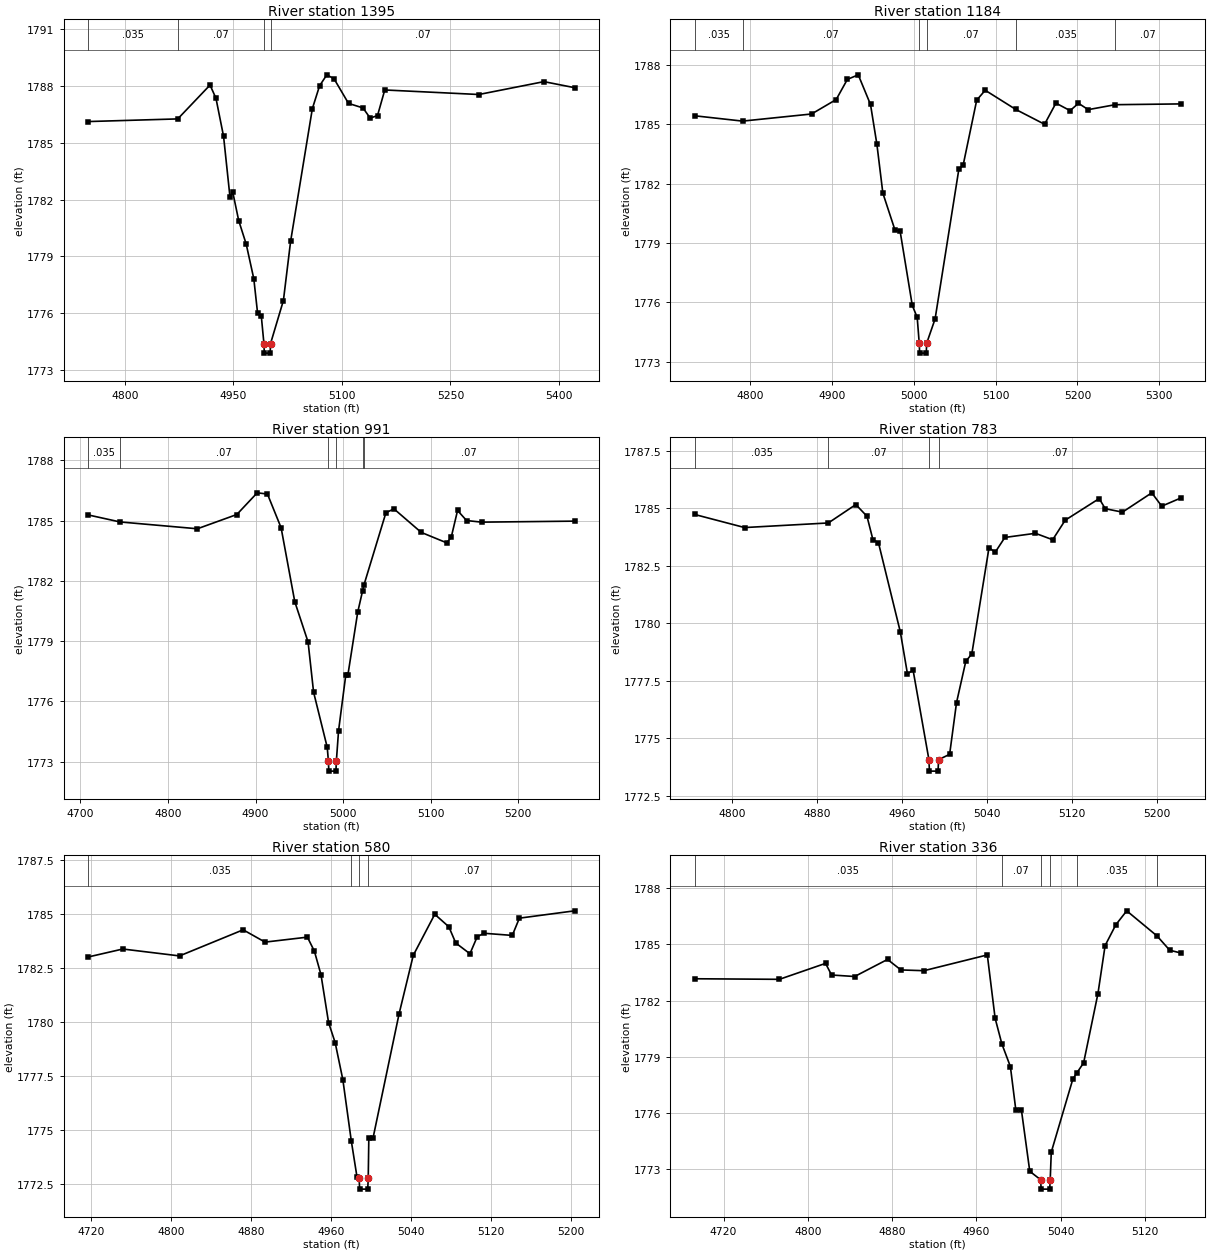
Type RM Length L Ch R = 1,1395,211,211,211
BEGIN DESCRIPTION:
Elm 01 32 1394.763
END DESCRIPTION:
XS GIS Cut Line= 3
      1552421.80      6831277.06      1552494.71      6831037.50
      1552484.29      6830615.63
#Sta/Elev= 30
  4749.3 1786.13  4873.2 1786.27  4917.8 1788.06  4926.0 1787.36  4936.5 1785.35
  4945.4 1782.13  4949.2 1782.40  4957.4 1780.90  4967.8 1779.65  4978.3 1777.82
  4983.5 1776.01  4988.7 1775.83  4992.3 1774.39  4992.8 1773.89  5000.9 1773.89
  5001.4 1774.39  5019.2 1776.67  5029.2 1779.81  5059.2 1786.81  5069.2 1788.02
  5079.2 1788.60  5089.2 1788.39  5109.2 1787.09  5129.2 1786.85  5139.2 1786.31
  5149.3 1786.45  5159.3 1787.80  5289.3 1787.56  5379.3 1788.24  5421.7 1787.92
#Mann=4,-1,0
  4749.3   0.035       0  4873.2    0.07       0  4992.3    0.07       0
  5001.4    0.07       0
Bank Sta=4992.3,5001.4
Exp/Cntr=0.3,0.1

Type RM Length L Ch R = 1,1184,193,193,193
BEGIN DESCRIPTION:
Elm 01 32 1183.575
END DESCRIPTION:
XS GIS Cut Line= 3
      1552541.58      6831313.55      1552697.83      6831079.17
      1552781.18      6830777.04
#Sta/Elev= 30
  4731.7 1785.43  4790.4 1785.16  4874.8 1785.52  4904.9 1786.25  4918.6 1787.27
  4931.9 1787.50  4946.9 1786.00  4954.7 1783.99  4962.0 1781.52  4977.0 1779.63
  4983.0 1779.62  4998.0 1775.84  5004.0 1775.24  5006.5 1773.93  5007.0 1773.43
  5015.1 1773.43  5015.6 1773.93  5025.9 1775.16  5055.0 1782.74  5060.2 1782.93
  5076.8 1786.22  5087.2 1786.72  5124.6 1785.75  5159.8 1785.00  5173.7 1786.07
  5191.0 1785.69  5201.3 1786.06  5213.2 1785.74  5246.2 1785.99  5326.8 1786.03
#Mann=6,-1,0
  4731.7   0.035       0  4790.4    0.07       0  5006.5    0.07       0
  5015.6    0.07       0  5124.6   0.035       0  5246.2    0.07       0
Bank Sta=5006.5,5015.6
Exp/Cntr=0.3,0.1

Type RM Length L Ch R = 1,991,208,208,208
BEGIN DESCRIPTION:
Elm 01 32 991.012
END DESCRIPTION:
XS GIS Cut Line= 3
      1552598.85      6831334.39      1552854.08      6831183.34
      1553104.09      6831115.62
#Sta/Elev= 30
  4708.8 1785.29  4745.2 1784.94  4833.6 1784.60  4878.6 1785.31  4901.9 1786.39
  4913.6 1786.33  4929.2 1784.65  4944.8 1780.97  4960.0 1778.96  4966.3 1776.46
  4981.9 1773.71  4983.2 1773.03  4983.7 1772.53  4991.8 1772.53  4992.3 1773.03
  4994.8 1774.54  5003.0 1777.30  5005.4 1777.30  5016.7 1780.45  5022.2 1781.50
  5023.8 1781.80  5048.9 1785.40  5058.1 1785.59  5089.2 1784.42  5118.3 1783.90
  5123.5 1784.18  5130.7 1785.51  5141.0 1785.01  5158.1 1784.93  5264.4 1784.98
#Mann=6,-1,0
  4708.8   0.035       0  4745.2    0.07       0  4983.2    0.07       0
  4992.3    0.07       0  5022.2   0.035       0  5023.8    0.07       0
Bank Sta=4983.2,4992.3
Exp/Cntr=0.3,0.1

Type RM Length L Ch R = 1,783,203,203,203
BEGIN DESCRIPTION:
Elm 01 32 783.06
END DESCRIPTION:
XS GIS Cut Line= 3
      1552630.04      6831462.99      1552859.29      6831391.67
      1553050.99      6831288.05
#Sta/Elev= 30
  4764.7 1784.72  4811.8 1784.15  4890.6 1784.35  4916.5 1785.15  4927.0 1784.64
  4932.6 1783.62  4937.8 1783.49  4958.4 1779.61  4965.1 1777.79  4970.4 1777.95
  4985.3 1774.06  4985.8 1773.56  4993.9 1773.56  4994.4 1774.06  5004.8 1774.29
  5011.3 1776.54  5020.0 1778.33  5025.7 1778.66  5041.9 1783.28  5047.6 1783.07
  5056.8 1783.72  5085.6 1783.90  5101.8 1783.62  5113.6 1784.47  5145.6 1785.41
  5151.3 1784.97  5167.5 1784.82  5195.1 1785.66  5204.5 1785.08  5222.7 1785.44
#Mann=4,-1,0
  4764.7   0.035       0  4890.6    0.07       0  4985.3    0.07       0
  4994.4    0.07       0
Bank Sta=4985.3,4994.4
Exp/Cntr=0.3,0.1

Type RM Length L Ch R = 1,580,244,244,244
BEGIN DESCRIPTION:
Elm 01 32 579.991
END DESCRIPTION:
XS GIS Cut Line= 3
      1552718.69      6831751.02      1552933.19      6831566.27
      1553072.84      6831417.70
#Sta/Elev= 30
  4716.9 1783.02  4751.6 1783.39  4808.4 1783.07  4872.1 1784.28  4894.0 1783.71
  4936.4 1783.94  4943.4 1783.29  4950.0 1782.20  4957.6 1779.98  4964.2 1779.05
  4971.9 1777.33  4980.3 1774.51  4986.1 1772.81  4988.2 1772.76  4988.7 1772.26
  4996.8 1772.26  4997.3 1772.76  4997.9 1774.65  5002.2 1774.65  5028.2 1780.39
  5042.4 1783.10  5063.9 1785.00  5078.0 1784.42  5084.9 1783.67  5099.1 1783.17
  5106.4 1783.96  5113.2 1784.12  5141.5 1784.02  5148.6 1784.82  5203.9 1785.16
#Mann=4,-1,0
  4716.9   0.035       0  4980.3    0.07       0  4988.2    0.07       0
  4997.3    0.07       0
Bank Sta=4988.2,4997.3
Exp/Cntr=0.3,0.1

Type RM Length L Ch R = 1,336,221,221,221
BEGIN DESCRIPTION:
Elm 01 32 335.956
END DESCRIPTION:
XS GIS Cut Line= 3
      1552989.52      6831959.35      1553134.85      6831688.36
      1553166.59      6831537.46
#Sta/Elev= 30
  4692.5 1783.16  4773.0 1783.13  4816.8 1783.98  4822.5 1783.36  4844.4 1783.28
  4875.6 1784.19  4888.3 1783.63  4910.2 1783.59  4970.3 1784.43  4977.7 1781.06
  4984.1 1779.69  4992.2 1778.48  4997.4 1776.15  5002.7 1776.15  5010.6 1772.90
  5020.9 1772.45  5021.4 1771.95  5029.5 1771.95  5030.0 1772.45  5031.0 1773.92
  5051.5 1777.82  5055.0 1778.12  5061.7 1778.68  5075.3 1782.37  5082.1 1784.93
  5092.3 1786.04  5102.6 1786.78  5131.4 1785.44  5143.4 1784.68  5154.2 1784.53
#Mann=6,-1,0
  4692.5   0.035       0  4984.1    0.07       0  5020.9    0.07       0
  5030.0    0.07       0  5055.0   0.035       0  5131.4    0.07       0
Bank Sta=5020.9,5030
Exp/Cntr=0.3,0.1

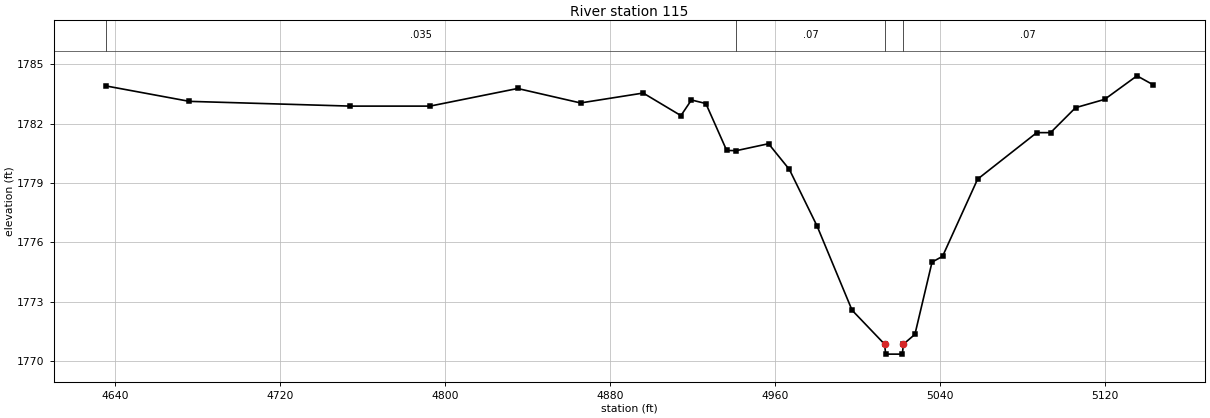
Type RM Length L Ch R = 1,115,0,0,0
BEGIN DESCRIPTION:
Elm 01 32 1.0
END DESCRIPTION:
XS GIS Cut Line= 3
      1553283.71      6832085.04      1553358.34      6831636.40
      1553312.58      6831609.46
#Sta/Elev= 30
  4635.5 1783.91  4676.0 1783.13  4754.1 1782.89  4792.7 1782.89  4835.2 1783.78
  4865.7 1783.05  4896.1 1783.55  4914.4 1782.41  4919.5 1783.20  4926.5 1783.02
  4936.6 1780.65  4941.3 1780.64  4956.9 1780.99  4967.0 1779.69  4980.4 1776.84
  4997.4 1772.58  5013.2 1770.86  5013.7 1770.36  5021.8 1770.36  5022.3 1770.86
  5027.9 1771.36  5036.2 1775.01  5041.3 1775.30  5058.3 1779.20  5087.0 1781.55
  5093.7 1781.55  5105.8 1782.81  5119.9 1783.23  5135.6 1784.42  5143.4 1783.97
#Mann=4,-1,0
  4635.5   0.035       0  4941.3    0.07       0  5013.2    0.07       0
  5022.3    0.07       0
Bank Sta=5013.2,5022.3
Exp/Cntr=0.3,0.1

Chan Stop Cuts=-1