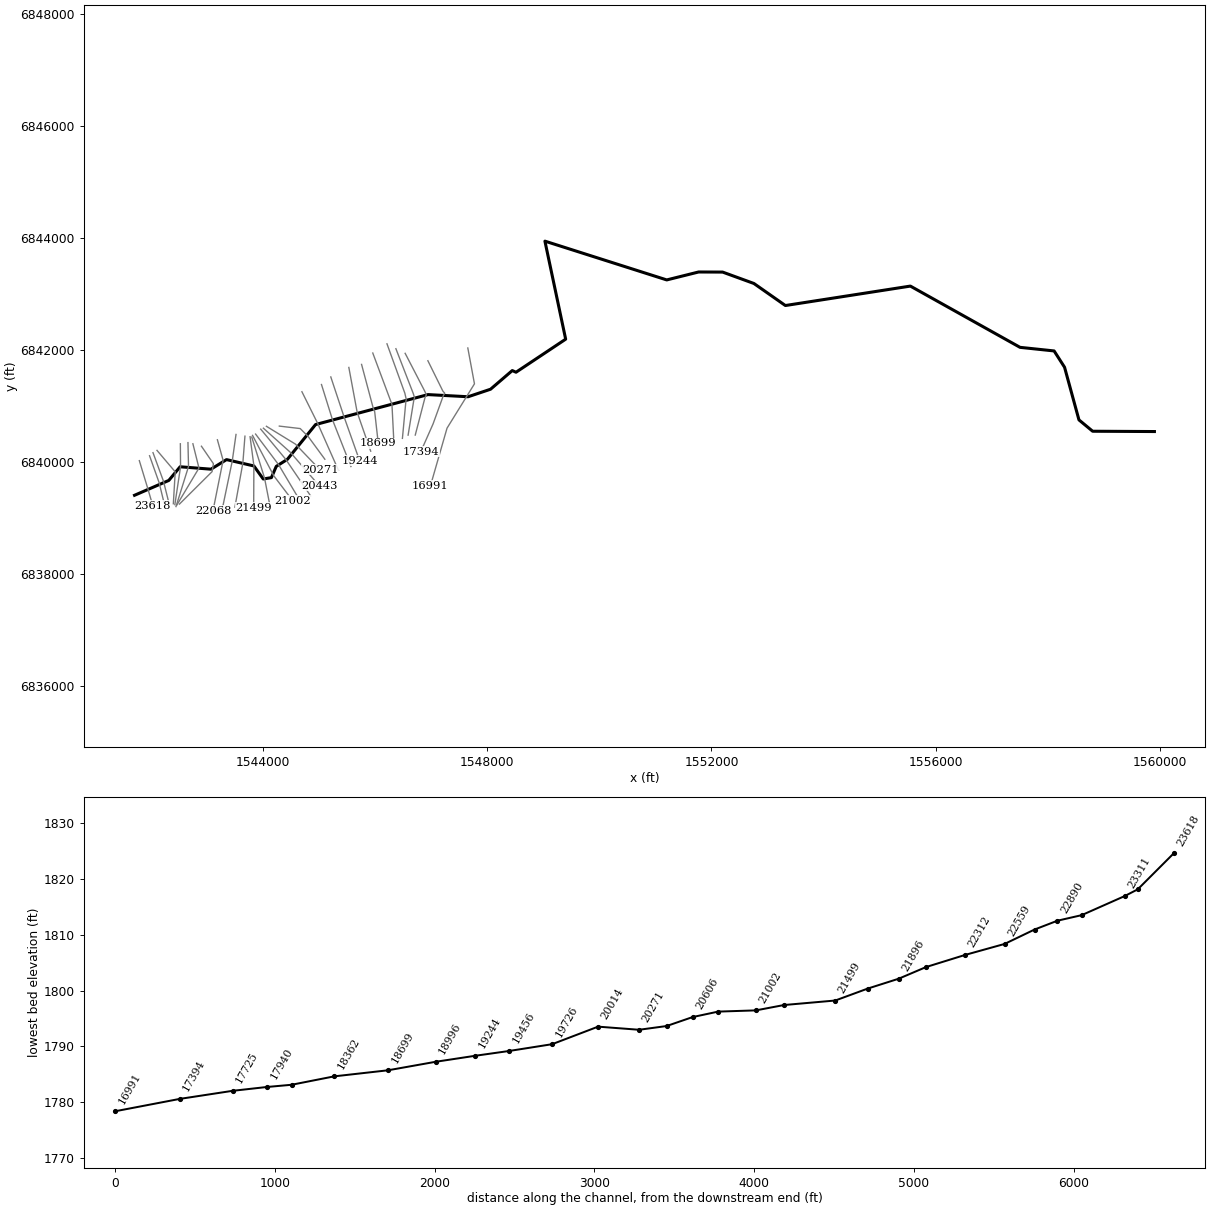
--- Elm 01 33.prj (project) ---

Proj Title=Elm 01 33 Base Level Engineering
Current Plan=p01
Default Exp/Contr=0.3,0.1
English Units
Geom File=g01
Flow File=f01
Plan File=p01
Y Axis Title=Elevation
X Axis Title(PF)=Main Channel Distance
X Axis Title(XS)=Station
BEGIN DESCRIPTION:
Elm 01 33
END DESCRIPTION:
DSS Export Rating Curves= 0
DSS Export Rating Curve Sorted= 0
DSS Export Volume Flow Curves= 0
DXF OffsetX= 0
DXF OffsetY= 0
DXF ScaleX= 1
DXF ScaleY= 10

--- Elm 01 33.p01 (plan) ---

Plan Title=Multiple Run
Program Version=4.10
Short Identifier=Multiple
Geom File=g01
Flow File=f01
Subcritical Flow
K Sum by GR= 0
Std Step Tol= 0.01
Critical Tol= 0.01
Num of Std Step Trials= 20
Max Error Tol= 0.3
Flow Tol Ratio= 0.001
Split Flow NTrial= 30
Split Flow Tol= 0.02
Split Flow Ratio= 0.02
Log Output Level= 0
Friction Slope Method= 1
Unsteady Friction Slope Method= 2
Unsteady Bridges Friction Slope Method= 1
Parabolic Critical Depth
Global Vel Dist= 1 , 1 , 1
Global Log Level= 0
CheckData=True
Encroach Param=-1 ,0,0, 0
BEGIN DESCRIPTION:
Multiple Run
END DESCRIPTION:
Computation Interval=1HOUR
Output Interval=1HOUR
Run HTab= 0
Run UNet= 0
Run PostProcess= 0
Run WQNet= 0
UNET Theta= 1
UNET Theta Warmup= 1
UNET ZTol= 0.02
UNET ZSATol= 0.05
UNET MxIter= 20
UNET MaxInSteps= 0
UNET DtIC= 0
UNET DtMin= 0
UNET MaxCRTS= 20
UNET WFStab= 2
UNET SFStab= 1
UNET WFX= 1
UNET SFX= 1
UNET DSS MLevel= 4
UNET DZMax Abort= 100
UNET Convert EG Bridges= 0
UNET Use Existing IB Tables=-1
UNET Froude Reduction=False
UNET Froude Limit= 1
UNET Froude Power= 10
UNET Time Slicing=0,0, 5
UNET Junction Losses=0
Instantaneous Interval=1HOUR
Write IC File= 0
Write IC File at Sim End=0
Echo Input=False
Echo Parameters=False
Echo Output=False
Write Detailed= 0
WQ AD Non Conservative
WQ ULTIMATE=-1
WQ Max Comp Step=1HOUR
WQ Output Interval=15MIN
WQ Output Selected Increments= 0
WQ Output face flow=0
WQ Output face velocity=0
WQ Output face area=0
WQ Output face dispersion=0
WQ Output cell volume=0
WQ Output cell surface area=0
WQ Output cell continuity=0
WQ Output cumulative cell continuity=0
WQ Output face conc=0
WQ Output face dconc_dx=0
WQ Output face courant=0
WQ Output face peclet=0
WQ Output face adv mass=0
WQ Output face disp mass=0
WQ Output cell mass=0
WQ Output cell source sink temp=0
WQ Output cell source sink nsm=0
WQ Output MaxMinRange=-1
WQ Daily Max Min Mean=-1
WQ Daily Range=0
WQ Daily Time=0
WQ Create Restart=0
WQ Fixed Restart=0
WQ System Summary=0
WQ Use Fixed Temperature=0
Sorting and Armoring Iterations= 10
XS Update Threshold= 0.02
Hydraulics Update Threshold= 0.02
Energy Slope Method= 1
Volume Change Method= 0
XS Weighting Method= 0
Number of US Weighted Cross Sections= 1
Number of DS Weighted Cross Sections= 1
Upstream XS Weight=0.25
Main XS Weight=0.5
Downstream XS Weight=0.25
Number of DS XS's Weighted with US Boundary= 1
Upstream Boundary Weight= 1
Weight of XSs Associated with US Boundary= 0
Number of US XS's Weighted with DS Boundary= 1
Downstream Boundary Weight= 0.5
Weight of XSs Associated with DS Boundary= 0.5
Sediment Output Level= 4
Mass or Volume Output= 0
Output Increment Type= 1
Profile and TS Output Increment= 10
XS Output Flag= 0
XS Output Increment= 10
Disregard all LS=0
Disregard all Conn=0
Disregard all Breaches=0
Disregard all Pumps=0

--- Elm 01 33.f01 (steady flow) ---

Flow Title=Multiple
Number of Profiles=7
Profile Names=10-year,25-year,50-year,1pct_min,100-year,1pct_plu,500-year
River Rch & RM= Elm 01 33,Reach-1,23618
     257     357     439     335     537     740     815
River Rch & RM= Elm 01 33,Reach-1,16991
     508     732     924     721    1160    1590    1840
River Rch & RM= Elm 01 33,Reach-1,14854
     609     885    1120     881    1410    1940    2270
River Rch & RM= Elm 01 33,Reach-1,13773
     653     951    1210     951    1520    2100    2450
River Rch & RM= Elm 01 33,Reach-1,12257
     650     945    1200     941    1510    2070    2420
River Rch & RM= Elm 01 33,Reach-1,8893
     718    1050    1330    1040    1670    2300    2690
River Rch & RM= Elm 01 33,Reach-1,4481
     785    1140    1460    1140    1830    2520    2950
Boundary for River Rch & Prof#=Elm 01 33,Reach-1,1
Up Type=0
Dn Type=3
Dn Slope=0.005
Boundary for River Rch & Prof#=Elm 01 33,Reach-1,2
Up Type=0
Dn Type=3
Dn Slope=0.005
Boundary for River Rch & Prof#=Elm 01 33,Reach-1,3
Up Type=0
Dn Type=3
Dn Slope=0.005
Boundary for River Rch & Prof#=Elm 01 33,Reach-1,4
Up Type=0
Dn Type=3
Dn Slope=0.005
Boundary for River Rch & Prof#=Elm 01 33,Reach-1,5
Up Type=0
Dn Type=3
Dn Slope=0.005
Boundary for River Rch & Prof#=Elm 01 33,Reach-1,6
Up Type=0
Dn Type=3
Dn Slope=0.005
Boundary for River Rch & Prof#=Elm 01 33,Reach-1,7
Up Type=0
Dn Type=3
Dn Slope=0.005

--- Elm 01 33.g01 (geometry) ---

Geom Title=Existing Conditions
Program Version=4.10

River Reach=Elm 01 33       ,Reach-1
Reach XY= 30
      1541703.46      6839399.76      1542314.88      6839664.86
      1542516.85      6839908.82      1543067.41      6839865.82
      1543345.33      6840036.84      1543833.61      6839923.34
      1544000.27       6839690.7      1544146.11        6839715.
      1544232.91      6839916.39      1544430.83      6840041.39
       1544934.3      6840662.92       1546940.8      6841197.85
      1547656.52      6841159.45      1548057.28      6841293.87
      1548444.68      6841626.89      1548511.66      6841597.31
      1549397.77      6842187.68      1549027.31      6843938.38
      1551201.59      6843245.81      1551770.22      6843387.48
      1552199.06      6843385.74      1552757.29      6843182.16
      1553318.86      6842788.54      1555549.48      6843135.65
      1557506.55      6842041.75      1558114.82      6841977.53
      1558301.17      6841686.42      1558558.23      6840746.01
      1558802.57       6840543.4        1559905.        6840538.

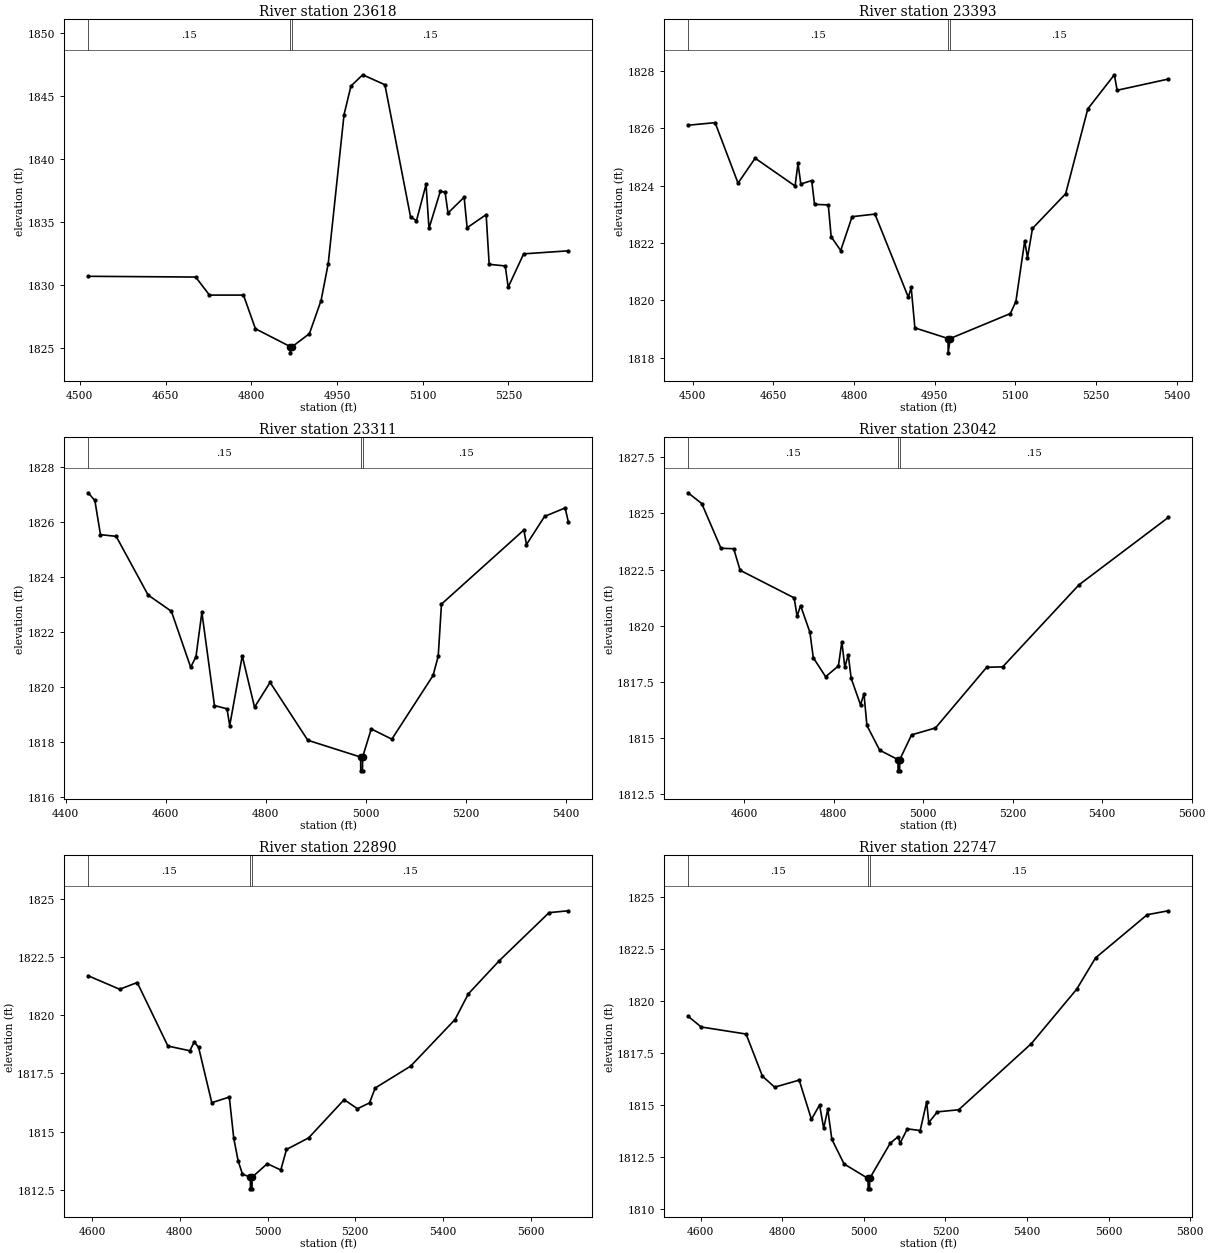
Type RM Length L Ch R = 1 ,23618   ,225,225,225
BEGIN DESCRIPTION:
Elm 01 33 23618.035
END DESCRIPTION:
XS GIS Cut Line= 3
      1541789.05      6840018.21      1541929.85      6839553.58
        1542030.        6839213.
#Sta/Elev= 30
  4514.5 1830.69  4702.8 1830.63  4726.8  1829.2  4786.4  1829.2  4807.3 1826.53
    4868 1825.12  4868.2 1824.62    4872 1825.12  4901.8 1826.14  4922.2 1828.77
  4934.7 1831.69  4962.4 1843.51  4974.5 1845.78  4995.1 1846.67  5033.9 1845.88
  5078.8  1835.4  5089.2  1835.1  5105.9 1837.97  5111.1 1834.49  5130.9 1837.43
  5139.2 1837.36  5144.4 1835.71  5172.6 1836.96  5177.8 1834.54  5211.1 1835.58
  5216.4 1831.64  5244.5 1831.51  5249.7 1829.83  5276.8 1832.47    5355 1832.71
#Mann= 3 ,-1 , 0
  4514.5     .15       0    4868     .05       0    4872     .15       0
Bank Sta=4868,4872
XS Rating Curve= 0 ,0
Exp/Cntr=0.3,0.1

Type RM Length L Ch R = 1 ,23393   ,82,82,82
BEGIN DESCRIPTION:
Elm 01 33 23392.61
END DESCRIPTION:
XS GIS Cut Line= 3
      1541971.44       6840105.7      1542141.94      6839626.21
      1542233.02      6839252.55
#Sta/Elev= 30
  4491.1 1826.11  4541.5  1826.2  4584.2 1824.09    4616 1824.96  4690.3 1823.99
  4695.7 1824.78    4701 1824.06  4721.2 1824.18  4726.5 1823.35  4752.1 1823.33
  4757.4 1822.22  4775.2 1821.74  4796.4 1822.92  4838.9 1823.01    4901 1820.11
  4906.3 1820.45  4913.2 1819.04  4974.9 1818.67  4975.1 1818.17  4978.9 1818.67
  5090.8 1819.54  5101.1 1819.96  5117.5 1822.07  5122.7 1821.49    5132 1822.51
  5193.7 1823.72  5234.9 1826.68  5284.3 1827.87  5289.5 1827.33  5384.6 1827.72
#Mann= 3 ,-1 , 0
  4491.1     .15       0  4974.9     .05       0  4978.9     .15       0
Bank Sta=4974.9,4978.9
XS Rating Curve= 0 ,0
Exp/Cntr=0.3,0.1

Type RM Length L Ch R = 1 ,23311   ,269,269,269
BEGIN DESCRIPTION:
Elm 01 33 23310.68
END DESCRIPTION:
XS GIS Cut Line= 3
      1542033.11      6840160.64      1542219.56      6839652.13
      1542321.25      6839245.37
#Sta/Elev= 30
  4444.7 1827.05  4458.2 1826.77  4469.4 1825.53  4500.8 1825.47  4564.7 1823.34
  4611.3 1822.75  4649.9 1820.72  4660.5  1821.1  4672.3 1822.71  4697.5 1819.33
  4722.6 1819.21    4728  1818.6  4753.1 1821.13  4777.7 1819.27  4808.8 1820.17
  4884.2 1818.07  4989.9 1817.46  4990.2 1816.96  4993.7 1816.96  4993.9 1817.46
  5011.2 1818.48  5052.4 1818.11  5134.9 1820.42  5145.2 1821.12  5151.7 1823.01
  5316.6  1825.7  5321.8 1825.17  5357.9 1826.19  5399.1  1826.5  5405.6 1825.99
#Mann= 3 ,-1 , 0
  4444.7     .15       0  4989.9     .05       0  4993.9     .15       0
Bank Sta=4989.9,4993.9
XS Rating Curve= 0 ,0
Exp/Cntr=0.3,0.1

Type RM Length L Ch R = 1 ,23042   ,152,152,152
BEGIN DESCRIPTION:
Elm 01 33 23042
END DESCRIPTION:
XS GIS Cut Line= 3
      1542104.28      6840201.32      1542429.74      6839818.24
      1542395.84      6839248.71
#Sta/Elev= 30
  4474.5 1825.92  4505.2 1825.44  4548.1 1823.45  4576.6 1823.43  4590.9 1822.47
  4711.7 1821.24  4718.3 1820.42    4726  1820.9  4746.9 1819.71  4754.4 1818.58
    4782 1817.73  4810.6 1818.21  4818.3 1819.29  4824.9 1818.15  4832.6 1818.71
  4839.1 1817.66    4860 1816.48  4867.7 1816.97  4874.3 1815.56  4902.8 1814.46
  4943.7 1814.04  4943.9 1813.54  4947.4 1813.54  4947.7 1814.04    4974 1815.14
  5027.5 1815.45  5141.9 1818.15  5177.8 1818.17  5348.1 1821.82  5547.7 1824.82
#Mann= 3 ,-1 , 0
  4474.5     .15       0  4943.7     .05       0  4947.7     .15       0
Bank Sta=4943.7,4947.7
XS Rating Curve= 0 ,0
Exp/Cntr=0.3,0.1

Type RM Length L Ch R = 1 ,22890   ,143,143,143
BEGIN DESCRIPTION:
Elm 01 33 22890.15
END DESCRIPTION:
XS GIS Cut Line= 3
      1542521.26      6840319.96      1542524.65      6839909.77
      1542423.04      6839232.35
#Sta/Elev= 30
  4590.8 1821.69  4662.8 1821.11  4702.8  1821.4  4772.8 1818.67  4822.8 1818.47
  4832.8 1818.85  4842.8 1818.61  4872.8 1816.24  4912.8 1816.48  4922.8 1814.73
  4932.8 1813.75  4942.8 1813.17  4960.8 1813.04    4961 1812.54  4964.5 1812.54
  4964.8 1813.04  4999.4 1813.62  5030.2 1813.35  5043.2 1814.23  5093.8 1814.73
  5174.7 1816.37    5205 1815.98  5232.5 1816.23  5245.5 1816.87  5326.4 1817.81
  5427.5 1819.81  5457.8 1820.91  5528.6 1822.34    5642  1824.4    5686 1824.48
#Mann= 3 ,-1 , 0
  4590.8     .15       0  4960.8     .05       0  4964.8     .15       0
Bank Sta=4960.8,4964.8
XS Rating Curve= 0 ,0
Exp/Cntr=0.3,0.1

Type RM Length L Ch R = 1 ,22747   ,188,188,188
BEGIN DESCRIPTION:
Elm 01 33 22746.82
END DESCRIPTION:
XS GIS Cut Line= 3
      1542656.86      6840340.29      1542667.03      6839913.16
       1542443.3      6839197.89
#Sta/Elev= 30
  4569.3 1819.28  4601.6 1818.76  4711.6 1818.42  4751.6 1816.39  4781.6 1815.86
  4841.7  1816.2  4871.7 1814.31  4891.7    1815  4901.7 1813.88  4911.7 1814.79
  4921.7 1813.35  4951.7 1812.16  5010.4 1811.46  5010.7 1810.96  5014.2 1810.96
  5014.4 1811.46  5064.8 1813.16  5083.8 1813.47  5089.1 1813.17  5106.7 1813.85
  5138.2 1813.77    5154 1815.15  5159.2 1814.15  5180.1 1814.67  5232.5 1814.77
  5410.6 1817.96  5521.6 1820.58  5567.8 1822.09  5694.4 1824.17    5746 1824.36
#Mann= 3 ,-1 , 0
  4569.3     .15       0  5010.4     .05       0  5014.4     .15       0
Bank Sta=5010.4,5014.4
XS Rating Curve= 0 ,0
Exp/Cntr=0.3,0.1

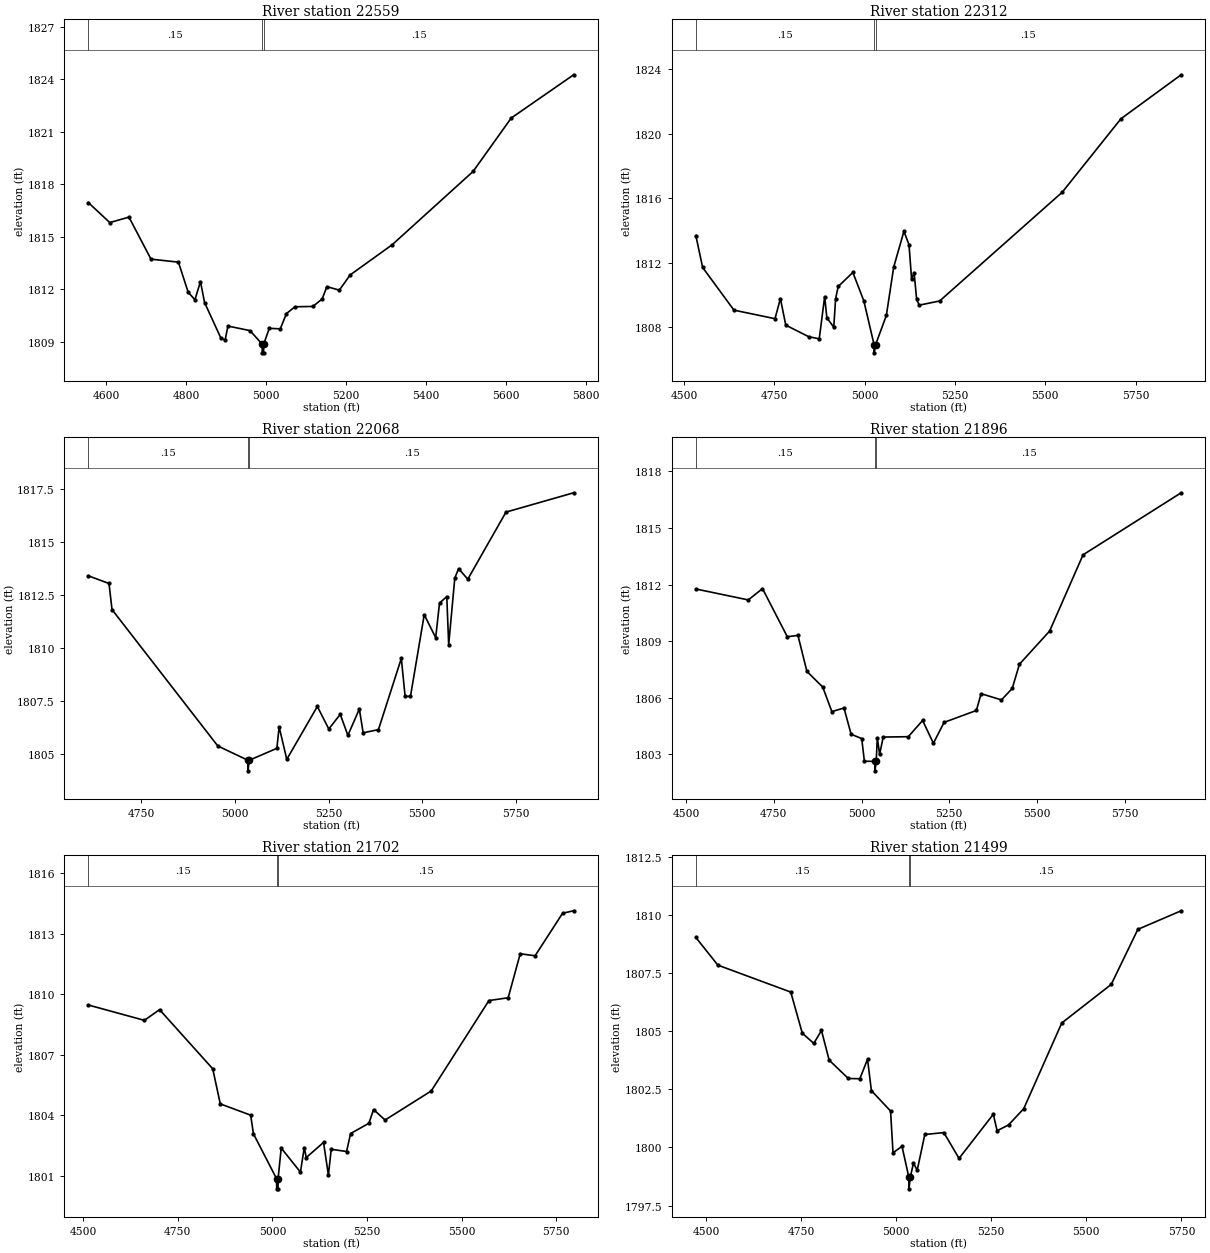
Type RM Length L Ch R = 1 ,22559   ,247,247,247
BEGIN DESCRIPTION:
Elm 01 33 22558.7
END DESCRIPTION:
XS GIS Cut Line= 3
      1542745.01      6840319.92      1542853.48      6839886.04
      1542460.23      6839228.37
#Sta/Elev= 30
  4555.2 1816.95  4608.7 1815.81  4656.7 1816.12  4711.8 1813.72  4780.4 1813.55
  4804.6 1811.84  4821.6  1811.4  4835.5 1812.44  4845.8 1811.24    4887 1809.19
  4897.3 1809.11  4904.1  1809.9  4959.2 1809.64  4989.7 1808.87  4989.9 1808.37
  4993.4 1808.37  4993.7 1808.87  5007.6 1809.77  5035.1 1809.74  5050.4 1810.61
  5071.8    1811  5116.7 1811.02  5139.9 1811.45  5151.6 1812.15  5182.7 1811.95
  5209.9 1812.82  5314.7 1814.54  5517.2 1818.73  5612.6 1821.78  5768.7 1824.25
#Mann= 3 ,-1 , 0
  4555.2     .15       0  4989.7     .05       0  4993.7     .15       0
Bank Sta=4989.7,4993.7
XS Rating Curve= 0 ,0
Exp/Cntr=0.3,0.1

Type RM Length L Ch R = 1 ,22312   ,244,244,244
BEGIN DESCRIPTION:
Elm 01 33 22312.32
END DESCRIPTION:
XS GIS Cut Line= 4
      1542897.54      6840275.88      1543111.11      6839964.01
      1543087.38      6839821.63      1542504.83      6839242.46
#Sta/Elev= 30
  4532.6 1813.68  4551.4  1811.7  4638.1 1809.05  4751.8 1808.52  4766.7 1809.77
  4781.6 1808.12  4845.2  1807.4  4874.3 1807.27  4889.3 1809.89  4895.3 1808.58
  4914.5 1807.99  4919.6 1809.77  4926.8 1810.52  4967.4 1811.39  4997.8 1809.62
  5026.2  1806.9  5026.5  1806.4  5030.2  1806.9  5060.1 1808.72  5080.4 1811.72
  5108.7 1813.94  5122.8 1813.12  5129.9 1810.99    5137 1811.36    5144 1809.72
  5151.1 1809.36  5207.7 1809.62  5547.1 1816.37  5709.7 1820.93  5876.4 1823.66
#Mann= 3 ,-1 , 0
  4532.6     .15       0  5026.2     .05       0  5030.2     .15       0
Bank Sta=5026.2,5030.2
XS Rating Curve= 0 ,0
Exp/Cntr=0.3,0.1

Type RM Length L Ch R = 1 ,22068   ,172,172,172
BEGIN DESCRIPTION:
Elm 01 33 22067.91
END DESCRIPTION:
XS GIS Cut Line= 3
       1543182.3      6840391.13        1543284.      6840025.02
      1543104.33      6839126.69
#Sta/Elev= 30
  4608.5 1813.41  4663.6 1813.05  4671.7 1811.82  4954.2  1805.4  5034.4 1804.73
  5034.7 1804.23  5038.4 1804.73  5111.9 1805.29    5118  1806.3  5138.4 1804.77
    5220 1807.26  5250.6  1806.2  5281.2 1806.89  5301.6  1805.9  5332.2 1807.14
  5342.4 1806.02  5383.2 1806.17  5444.3 1809.52  5454.5 1807.73  5468.8 1807.74
  5505.5 1811.58  5536.1  1810.5  5546.3 1812.13  5565.7 1812.43  5570.8 1810.17
  5587.1  1813.3  5597.3 1813.75  5621.8 1813.25  5723.8 1816.41  5904.6 1817.32
#Mann= 3 ,-1 , 0
  4608.5     .15       0  5034.4     .05       0  5038.4     .15       0
Bank Sta=5034.4,5038.4
XS Rating Curve= 0 ,0
Exp/Cntr=0.3,0.1

Type RM Length L Ch R = 1 ,21896   ,194,194,194
BEGIN DESCRIPTION:
Elm 01 33 21895.68
END DESCRIPTION:
XS GIS Cut Line= 3
      1543514.51      6840486.02      1543446.71      6840008.08
      1543263.66      6839126.71
#Sta/Elev= 30
  4527.8 1811.77  4677.3 1811.19  4717.7 1811.79  4788.4 1809.24  4818.7 1809.31
  4844.3  1807.4  4889.4 1806.57  4915.3 1805.27    4950 1805.46  4970.2 1804.07
  5000.5 1803.84    5008 1802.64  5037.8 1802.63  5038.1 1802.13  5041.8 1802.63
  5044.9 1803.88  5051.5 1803.01  5061.7 1803.92  5133.2 1803.94    5174  1804.8
  5204.7 1803.59  5235.2  1804.7  5327.2 1805.33  5340.6 1806.22  5398.7 1805.89
  5429.4  1806.5  5449.8 1807.78  5535.9 1809.54  5631.1 1813.58  5910.7 1816.87
#Mann= 3 ,-1 , 0
  4527.8     .15       0  5037.8     .05       0  5041.8     .15       0
Bank Sta=5037.8,5041.8
XS Rating Curve= 0 ,0
Exp/Cntr=0.3,0.1

Type RM Length L Ch R = 1 ,21702   ,203,203,203
BEGIN DESCRIPTION:
Elm 01 33 21701.97
END DESCRIPTION:
XS GIS Cut Line= 3
      1543673.84       6840455.5      1543636.55      6839974.18
      1543494.18      6839187.73
#Sta/Elev= 30
  4513.7 1809.47  4661.6 1808.71  4701.8 1809.24  4842.2 1806.31  4862.2 1804.57
  4942.5 1804.01  4949.7 1803.09  5010.9 1800.86  5011.2 1800.36  5014.7 1800.36
  5014.9 1800.86  5023.1 1802.38  5073.9 1801.19    5084  1802.4  5089.3 1801.91
  5134.9 1802.66  5147.8 1801.04  5155.2 1802.32  5195.8 1802.21  5206.4  1803.1
  5254.8 1803.61    5267 1804.29  5297.5 1803.77  5419.4 1805.21  5571.8 1809.69
  5622.7 1809.83  5654.5 1812.01  5693.8 1811.91  5766.5 1814.02  5795.7 1814.14
#Mann= 3 ,-1 , 0
  4513.7     .15       0  5010.9     .05       0  5014.9     .15       0
Bank Sta=5010.9,5014.9
XS Rating Curve= 0 ,0
Exp/Cntr=0.3,0.1

Type RM Length L Ch R = 1 ,21499   ,321,321,321
BEGIN DESCRIPTION:
Elm 01 33 21499.17
END DESCRIPTION:
XS GIS Cut Line= 3
      1543765.36      6840445.41      1543833.17      6839930.11
      1543829.78      6839174.16
#Sta/Elev= 30
  4473.6 1809.04  4531.5 1807.85  4723.1 1806.69  4753.4 1804.92  4783.7 1804.48
  4803.8 1805.04    4824 1803.76  4874.4 1802.97  4904.7 1802.96  4924.9  1803.8
    4935 1802.45  4985.4 1801.57  4991.9 1799.77  5015.5 1800.05  5033.5 1798.72
  5033.7 1798.22  5037.5 1798.72  5045.5 1799.33  5055.5 1799.02  5075.5 1800.56
  5125.5 1800.64  5165.5 1799.53  5255.5 1801.43  5265.5 1800.72  5295.5 1800.97
  5335.5 1801.67  5435.5 1805.36  5565.5 1807.02  5635.5 1809.39  5749.3 1810.19
#Mann= 3 ,-1 , 0
  4473.6     .15       0  5033.5     .05       0  5037.5     .15       0
Bank Sta=5033.5,5037.5
XS Rating Curve= 0 ,0
Exp/Cntr=0.3,0.1

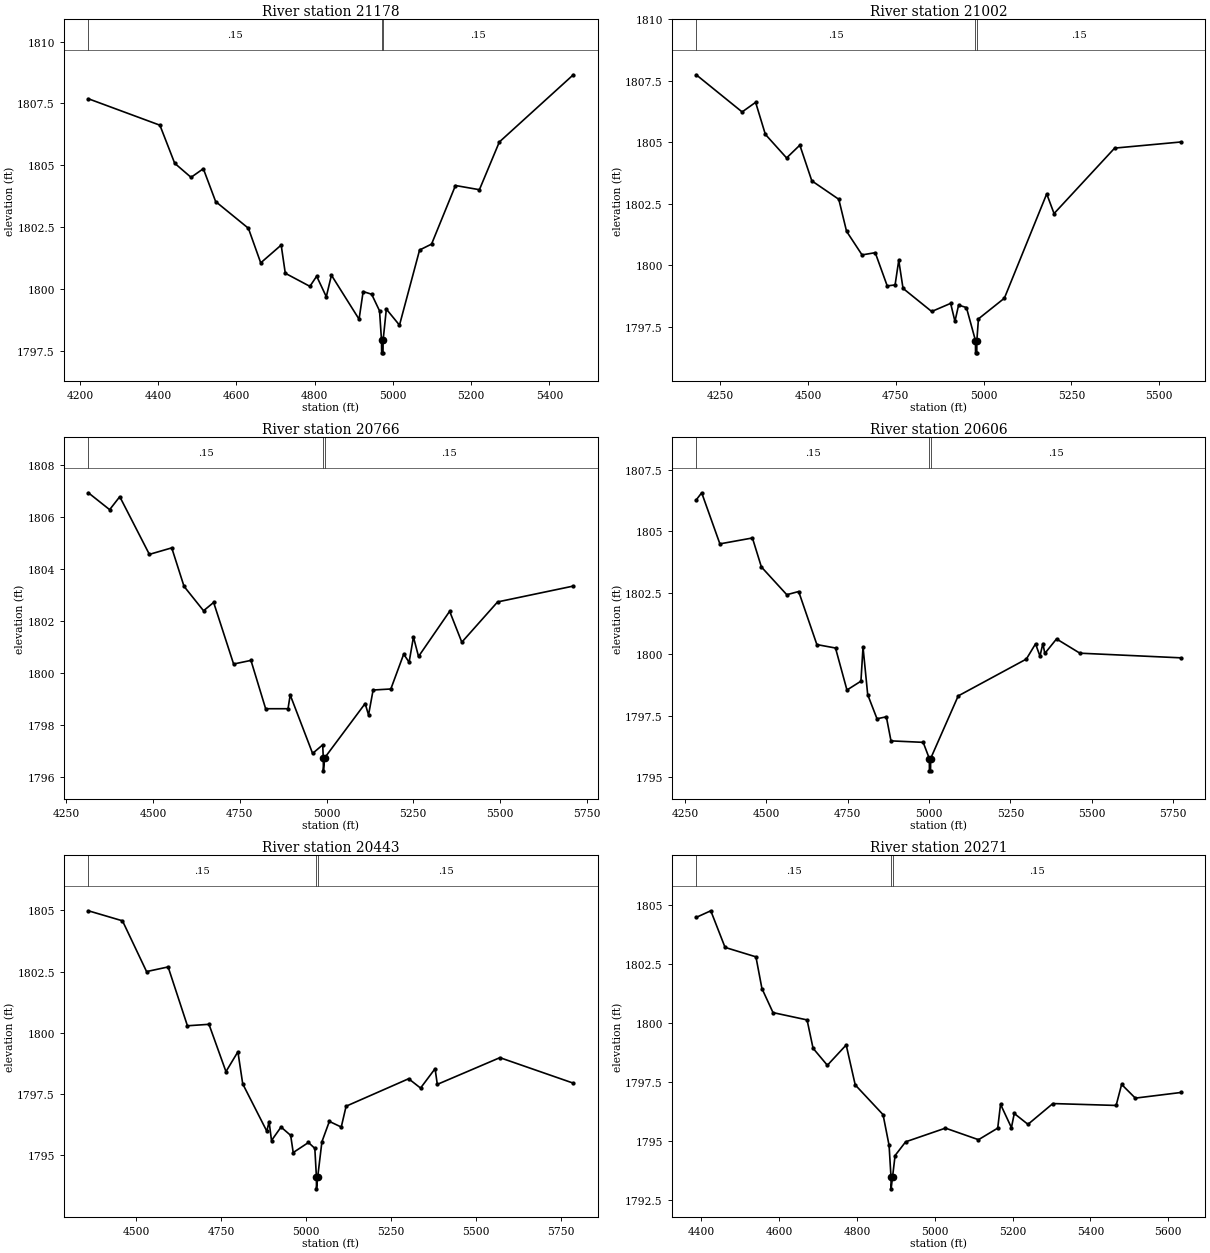
Type RM Length L Ch R = 1 ,21178   ,176,176,176
BEGIN DESCRIPTION:
Elm 01 33 21177.83
END DESCRIPTION:
XS GIS Cut Line= 3
      1543795.87      6840438.62        1544023.      6839709.76
      1544114.43      6839242.45
#Sta/Elev= 30
  4221.5 1807.69  4404.4 1806.62  4442.2 1805.08    4484 1804.51  4515.4 1804.86
  4546.9 1803.53  4630.6 1802.45  4662.1 1801.05  4714.4 1801.77  4724.9 1800.63
  4787.8  1800.1  4805.1 1800.51  4829.7 1799.68  4842.9 1800.55  4913.5 1798.77
  4923.9 1799.89  4945.7 1799.78  4965.8 1799.11  4970.9 1797.91  4971.2 1797.41
  4974.7 1797.41  4974.9 1797.91  4983.2 1799.18  5016.8 1798.53  5068.2 1801.57
  5098.8 1801.81  5159.9 1804.18  5221.1 1804.01    5272 1805.94  5461.1 1808.66
#Mann= 3 ,-1 , 0
  4221.5     .15       0  4970.9     .05       0  4974.9     .15       0
Bank Sta=4970.9,4974.9
XS Rating Curve= 0 ,0
Exp/Cntr=0.3,0.1

Type RM Length L Ch R = 1 ,21002   ,236,236,236
BEGIN DESCRIPTION:
Elm 01 33 21002.27
END DESCRIPTION:
XS GIS Cut Line= 3
      1543809.42      6840469.14      1544189.11      6839747.05
      1544530.73      6839297.19
#Sta/Elev= 30
    4182 1807.75  4312.7 1806.24  4351.1 1806.63  4378.8 1805.33  4439.3 1804.37
    4477 1804.89  4511.1 1803.44  4587.9 1802.69    4610 1801.39  4654.1 1800.43
  4691.7 1800.52  4725.8 1799.17  4748.2 1799.21  4758.6 1800.21  4770.8 1799.07
  4852.4 1798.13  4906.4 1798.46  4918.6 1797.73    4929 1798.39  4951.3 1798.29
    4977 1796.95  4977.3 1796.45  4980.8 1796.45    4981 1796.95  4985.5 1797.83
  5059.3 1798.67  5179.9 1802.91  5200.8 1802.11  5373.3 1804.77  5562.7 1805.02
#Mann= 3 ,-1 , 0
    4182     .15       0    4977     .05       0    4981     .15       0
Bank Sta=4977,4981
XS Rating Curve= 0 ,0
Exp/Cntr=0.3,0.1

Type RM Length L Ch R = 1 ,20766   ,160,160,160
BEGIN DESCRIPTION:
Elm 01 33 20765.8
END DESCRIPTION:
XS GIS Cut Line= 3
      1543863.67      6840492.84      1544273.86      6839947.06
      1544639.13      6839331.51
#Sta/Elev= 30
  4313.2 1806.93  4374.6 1806.28  4403.8 1806.78  4489.2 1804.56  4553.7 1804.81
  4589.1 1803.33  4645.4 1802.39  4674.5 1802.71  4732.1 1800.34  4782.1 1800.48
  4824.5 1798.62    4889 1798.62  4895.3 1799.15  4959.9  1796.9    4989 1797.23
  4990.7 1796.73    4991 1796.23  4994.7 1796.73  5111.4 1798.82  5121.2 1798.38
  5134.4 1799.34  5185.5 1799.38  5222.6 1800.72  5238.2 1800.41  5250.7 1801.38
  5265.4 1800.63  5355.1 1802.37  5390.2 1801.18  5493.4 1802.73  5711.7 1803.34
#Mann= 3 ,-1 , 0
  4313.2     .15       0  4990.7     .05       0  4994.7     .15       0
Bank Sta=4990.7,4994.7
XS Rating Curve= 0 ,0
Exp/Cntr=0.3,0.1

Type RM Length L Ch R = 1 ,20606   ,163,163,163
BEGIN DESCRIPTION:
Elm 01 33 20606.46
END DESCRIPTION:
XS GIS Cut Line= 3
      1543955.19      6840580.99      1544399.28      6840045.36
      1544846.74      6839387.74
#Sta/Elev= 30
    4284 1806.28  4300.8 1806.57  4356.8 1804.49  4456.8 1804.73  4484.4 1803.55
  4562.5 1802.42    4599 1802.55    4655 1800.39  4712.3 1800.25  4747.5 1798.54
  4790.5  1798.9  4796.9 1800.29  4811.3 1798.35  4839.9 1797.37  4868.6 1797.45
  4882.9 1796.47  4981.9 1796.41  5000.8 1795.75  5001.1 1795.25  5004.6 1795.25
  5004.8 1795.75  5089.6  1798.3  5299.1  1799.8  5327.4 1800.42    5341 1799.92
  5349.9 1800.43    5356 1800.03  5391.9 1800.62  5463.7 1800.04  5775.2 1799.85
#Mann= 3 ,-1 , 0
    4284     .15       0  5000.8     .05       0  5004.8     .15       0
Bank Sta=5000.8,5004.8
XS Rating Curve= 0 ,0
Exp/Cntr=0.3,0.1

Type RM Length L Ch R = 1 ,20443   ,172,172,172
BEGIN DESCRIPTION:
Elm 01 33 20443.4
END DESCRIPTION:
XS GIS Cut Line= 3
      1544002.67      6840597.92      1544484.03       6840167.4
      1544995.88       6839574.2
#Sta/Elev= 30
  4358.2 1804.98  4458.8 1804.57  4529.8  1802.5  4593.3 1802.69  4650.2 1800.29
  4713.7 1800.35  4763.8 1798.42    4799 1799.23  4813.2 1797.92  4884.2 1795.99
  4890.9 1796.38    4898 1795.61  4926.1 1796.16  4954.5 1795.82    4962 1795.12
  5006.9 1795.53  5025.7 1795.29  5030.3 1794.14  5030.6 1793.64  5034.3 1794.14
  5046.6 1795.56  5068.5 1796.39  5103.6 1796.16  5117.9 1797.01  5302.2 1798.13
  5337.3 1797.75  5380.1 1798.54  5386.7  1797.9  5571.2 1798.99  5787.5 1797.95
#Mann= 3 ,-1 , 0
  4358.2     .15       0  5030.3     .05       0  5034.3     .15       0
Bank Sta=5030.3,5034.3
XS Rating Curve= 0 ,0
Exp/Cntr=0.3,0.1

Type RM Length L Ch R = 1 ,20271   ,257,257,257
BEGIN DESCRIPTION:
Elm 01 33 20270.81
END DESCRIPTION:
XS GIS Cut Line= 3
      1544056.93       6840631.8      1544575.56      6840313.17
      1545015.86      6839852.55
#Sta/Elev= 30
  4387.1 1804.46  4424.5 1804.74  4461.2 1803.19  4540.5 1802.79  4555.9 1801.45
  4584.4 1800.43  4671.9 1800.12  4687.3 1798.92    4724  1798.2  4772.4 1799.06
  4795.6 1797.37  4867.1 1796.11  4882.6 1794.81  4887.5 1793.47  4887.8 1792.97
  4891.5 1793.47    4898 1794.38  4925.1 1794.96  5027.4 1795.54  5112.3 1795.05
  5161.7 1795.54  5168.9 1796.55  5196.9 1795.56  5204.2 1796.16  5239.4  1795.7
  5303.3 1796.58  5465.9  1796.5    5480 1797.39  5515.2 1796.81    5633 1797.05
#Mann= 3 ,-1 , 0
  4387.1     .15       0  4887.5     .05       0  4891.5     .15       0
Bank Sta=4887.5,4891.5
XS Rating Curve= 0 ,0
Exp/Cntr=0.3,0.1

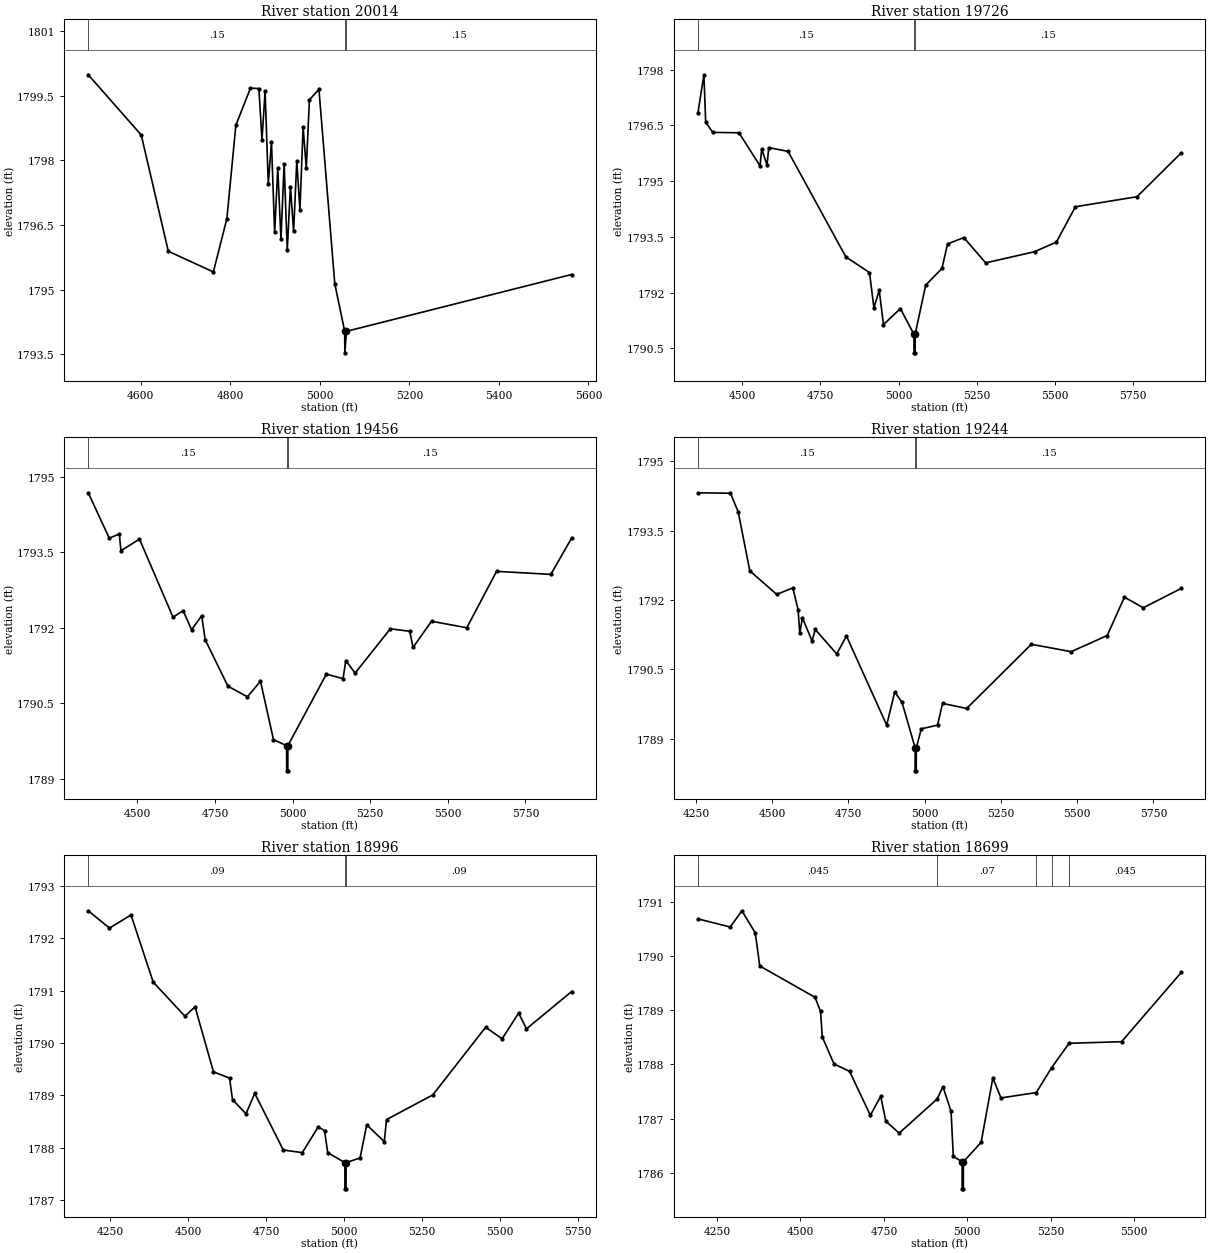
Type RM Length L Ch R = 1 ,20014   ,288,288,288
BEGIN DESCRIPTION:
Elm 01 33 20014.23
END DESCRIPTION:
XS GIS Cut Line= 4
      1544287.44      6840635.21      1544660.31      6840591.14
      1544802.69      6840448.77      1545100.13      6840043.15
#Sta/Elev= 30
  4482.6 1799.99    4601 1798.59  4661.4 1795.89  4762.1 1795.41  4792.3 1796.65
  4812.4 1798.82    4845 1799.68  4863.8 1799.67  4870.7 1798.48  4877.7 1799.61
  4884.8 1797.45  4891.9 1798.43    4899 1796.33    4906 1797.82  4913.1 1796.17
  4920.2 1797.91  4927.2 1795.92  4934.3 1797.39  4941.4 1796.35  4948.5 1797.99
  4955.5 1796.85  4962.6 1798.78  4969.7 1797.82  4976.7 1799.41    4998 1799.65
  5033.3 1795.14  5055.5 1794.03  5055.8 1793.53  5059.5 1794.03  5562.4 1795.35
#Mann= 3 ,-1 , 0
  4482.6     .15       0  5055.5     .05       0  5059.5     .15       0
Bank Sta=5055.5,5059.5
XS Rating Curve= 0 ,0
Exp/Cntr=0.3,0.1

Type RM Length L Ch R = 1 ,19726   ,270,270,270
BEGIN DESCRIPTION:
Elm 01 33 19726.33
END DESCRIPTION:
XS GIS Cut Line= 3
      1544690.81       6841248.8      1544975.57      6840675.89
      1545341.68      6839848.77
#Sta/Elev= 30
  4359.1 1796.84  4378.2 1797.86  4383.8 1796.59  4406.2 1796.31  4490.2  1796.3
  4557.4 1795.41    4563 1795.86  4579.8 1795.43  4585.4  1795.9  4647.1  1795.8
  4831.8 1792.96  4907.2 1792.54  4921.4 1791.59  4938.3 1792.06  4951.9 1791.14
  5005.9 1791.57  5049.2 1790.88  5049.5 1790.38    5053 1790.38  5053.2 1790.88
  5086.7  1792.2  5138.8 1792.65  5156.6 1793.31  5208.6 1793.48  5278.5  1792.8
  5434.6  1793.1  5504.5 1793.36  5565.2 1794.31  5762.1 1794.58  5903.4 1795.76
#Mann= 3 ,-1 , 0
  4359.1     .15       0  5049.2     .05       0  5053.2     .15       0
Bank Sta=5049.2,5053.2
XS Rating Curve= 0 ,0
Exp/Cntr=0.3,0.1

Type RM Length L Ch R = 1 ,19456   ,212,212,212
BEGIN DESCRIPTION:
Elm 01 33 19456
END DESCRIPTION:
XS GIS Cut Line= 3
      1545039.98       6841377.6       1545236.6      6840747.08
      1545565.43      6839913.13
#Sta/Elev= 30
  4341.8 1794.68  4409.3 1793.78  4441.8 1793.86    4447 1793.53  4506.8 1793.76
  4614.8 1792.21  4647.3 1792.34  4674.6 1791.96  4707.1 1792.24  4718.5 1791.76
  4791.8 1790.84  4854.6 1790.63  4896.5 1790.94  4938.4 1789.78  4980.8 1789.66
  4981.1 1789.16  4984.6 1789.16  4984.8 1789.66  5108.8 1791.08  5162.5 1790.99
  5171.5 1791.35  5201.3  1791.1  5314.9 1791.98  5377.5 1791.93    5388 1791.61
  5447.5 1792.13  5561.2    1792    5657 1793.12  5831.9 1793.06  5898.7 1793.78
#Mann= 3 ,-1 , 0
  4341.8     .15       0  4980.8     .05       0  4984.8     .15       0
Bank Sta=4980.8,4984.8
XS Rating Curve= 0 ,0
Exp/Cntr=0.3,0.1

Type RM Length L Ch R = 1 ,19244   ,248,248,248
BEGIN DESCRIPTION:
Elm 01 33 19243.59
END DESCRIPTION:
XS GIS Cut Line= 3
       1545206.1      6841513.17      1545439.99       6840808.1
      1545721.35      6840014.88
#Sta/Elev= 30
  4256.7 1794.32  4363.3 1794.31  4388.6 1793.91  4426.7 1792.63    4515 1792.12
  4567.7 1792.26  4585.1 1791.79  4590.4 1791.28  4599.3 1791.61  4630.9 1791.11
  4641.4 1791.36  4711.8 1790.83  4743.5 1791.22  4875.5 1789.29  4901.9 1790.01
  4925.9 1789.78  4968.6  1788.8  4968.8  1788.3  4972.3  1788.3  4972.6  1788.8
  4989.1 1789.21  5042.1 1789.29  5058.7 1789.76  5137.6 1789.65  5349.8 1791.04
  5480.3 1790.88  5598.5 1791.23  5654.9 1792.06  5716.7 1791.83  5841.2 1792.25
#Mann= 3 ,-1 , 0
  4256.7     .15       0  4968.6     .05       0  4972.6     .15       0
Bank Sta=4968.6,4972.6
XS Rating Curve= 0 ,0
Exp/Cntr=0.3,0.1

Type RM Length L Ch R = 1 ,18996   ,297,297,297
BEGIN DESCRIPTION:
Elm 01 33 18995.69
END DESCRIPTION:
XS GIS Cut Line= 3
      1545528.14      6841682.66      1545677.29      6840879.29
      1545917.96      6840187.77
#Sta/Elev= 30
  4179.3 1792.52  4247.2 1792.19  4316.3 1792.44  4387.5 1791.16  4489.2 1790.51
  4521.5 1790.69  4580.7 1789.45  4632.2 1789.33  4641.7 1788.92    4685 1788.65
  4712.9 1789.04  4804.5 1787.96  4865.5 1787.91  4916.3  1788.4  4936.7 1788.33
  4946.9 1787.91  5001.9 1787.72  5002.1 1787.22  5005.6 1787.22  5005.9 1787.72
  5050.7 1787.81  5071.9 1788.44  5128.2 1788.12  5135.4 1788.54  5283.7 1789.01
  5453.1  1790.3    5506 1790.08  5558.9 1790.57  5584.1 1790.27  5728.6 1790.98
#Mann= 3 ,-1 , 0
  4179.3     .09       0  5001.9     .07       0  5005.9     .09       0
Bank Sta=5001.9,5005.9
XS Rating Curve= 0 ,0
Exp/Cntr=0.3,0.1

Type RM Length L Ch R = 1 ,18699   ,337,337,337
BEGIN DESCRIPTION:
Elm 01 33 18699.4
END DESCRIPTION:
XS GIS Cut Line= 4
      1545755.27       6841736.9      1545962.04      6840960.64
      1545989.61      6840890.94      1546053.29      6840325.49
#Sta/Elev= 30
  4193.2 1790.69  4289.8 1790.54  4324.8 1790.84  4364.9 1790.43  4378.3 1789.82
  4543.9 1789.24  4560.3 1788.98  4565.5 1788.51  4600.5 1788.01  4647.4 1787.87
  4709.5 1787.06  4740.5 1787.41  4755.8 1786.95  4795.9 1786.73  4909.4 1787.36
  4926.8 1787.59  4951.2 1787.13  4957.9  1786.3  4984.2  1786.2  4984.4  1785.7
  4987.9  1785.7  4988.2  1786.2  5041.2 1786.56  5076.3 1787.75  5100.6 1787.38
  5206.4 1787.48  5252.3 1787.94  5304.6 1788.39  5461.8 1788.42  5640.5  1789.7
#Mann= 5 ,-1 , 0
  4193.2    .045       0  4909.4     .07       0  5206.4    .045       0
  5252.3     .07       0  5304.6    .045       0
Bank Sta=4984.2,4988.2
XS Rating Curve= 0 ,0
Exp/Cntr=0.3,0.1

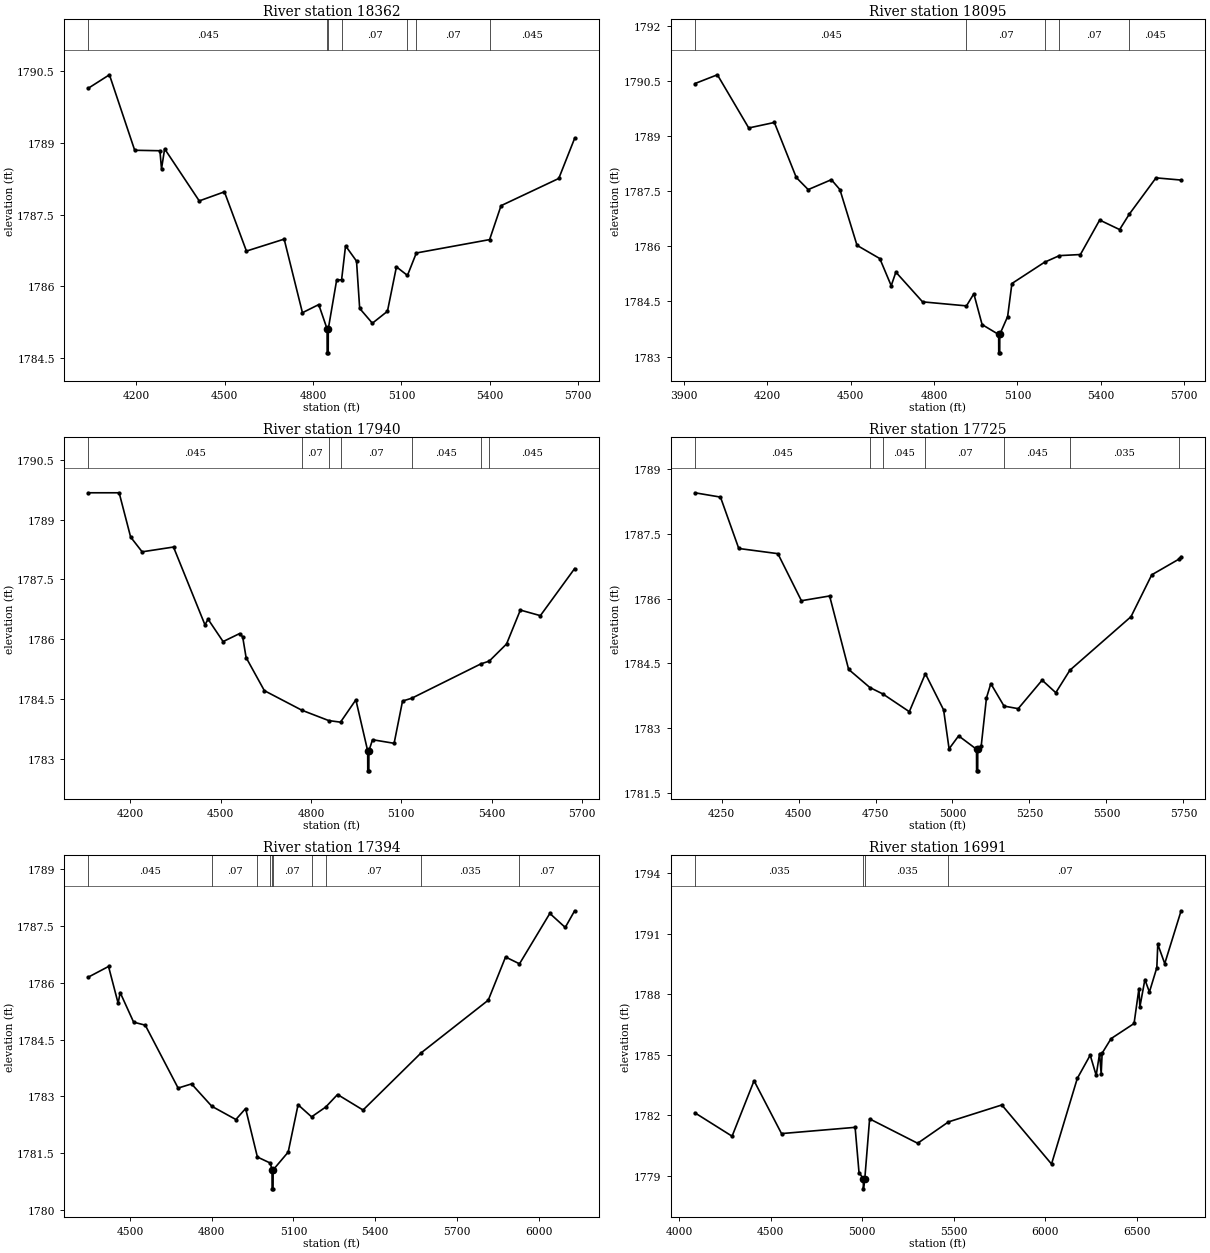
Type RM Length L Ch R = 1 ,18362   ,267,267,267
BEGIN DESCRIPTION:
Elm 01 33 18361.5
END DESCRIPTION:
XS GIS Cut Line= 3
      1545955.26      6841940.33      1546297.64      6841021.66
      1546331.61      6840353.32
#Sta/Elev= 30
  4037.9 1790.15  4109.2 1790.43  4194.9 1788.85  4280.5 1788.84  4285.9 1788.46
  4296.5 1788.88  4413.9 1787.79  4499.3 1787.98    4574 1786.74    4702 1786.99
    4764 1785.45  4819.3 1785.62  4847.7 1785.11  4847.9 1784.61  4851.4 1784.61
  4851.7 1785.11    4880 1786.13  4896.9 1786.14  4910.3 1786.85  4947.5 1786.53
  4958.2 1785.54  5001.3 1785.23  5052.4 1785.48  5082.9 1786.41  5120.3 1786.23
  5150.4  1786.7    5399 1786.98  5437.8 1787.69  5633.7 1788.26  5687.5  1789.1
#Mann= 7 ,-1 , 0
  4037.9    .045       0  4847.7     .07       0  4851.7    .045       0
  4896.9     .07       0  5120.3    .045       0  5150.4     .07       0
    5399    .045       0
Bank Sta=4847.7,4851.7
XS Rating Curve= 0 ,0
Exp/Cntr=0.3,0.1

Type RM Length L Ch R = 1 ,18095   ,155,155,155
BEGIN DESCRIPTION:
Elm 01 33 18095.04
END DESCRIPTION:
XS GIS Cut Line= 5
      1546208.63      6842104.81      1546527.38      6841223.49
      1546551.89      6841116.58      1546543.44      6841049.67
      1546484.25      6840416.05
#Sta/Elev= 30
  3938.6 1790.44  4019.6 1790.68  4132.5 1789.23  4224.8 1789.38  4303.7 1787.88
  4346.6 1787.55    4430 1787.82  4460.8 1787.55  4522.4 1786.03  4604.4 1785.67
  4645.5 1784.93  4662.3  1785.3  4758.4 1784.49  4916.5 1784.38    4943 1784.71
  4972.8 1783.87  5032.4  1783.6  5032.7  1783.1  5036.2  1783.1  5036.4  1783.6
  5064.7 1784.09  5080.1 1784.99  5197.6 1785.57    5251 1785.75  5326.7 1785.78
  5396.1 1786.72  5467.9 1786.46  5502.7 1786.88  5598.9 1787.87  5689.3 1787.81
#Mann= 5 ,-1 , 0
  3938.6    .045       0  4916.5     .07       0  5197.6    .045       0
    5251     .07       0  5502.7    .045       0
Bank Sta=5032.4,5036.4
XS Rating Curve= 0 ,0
Exp/Cntr=0.3,0.1

Type RM Length L Ch R = 1 ,17940   ,215,215,215
BEGIN DESCRIPTION:
Elm 01 33 17939.99
END DESCRIPTION:
XS GIS Cut Line= 5
       1546367.9      6842017.34      1546678.19      6841216.03
      1546701.04      6841140.31      1546685.67      6841088.53
      1546585.79      6840473.49
#Sta/Elev= 30
  4060.3 1789.67  4162.4 1789.67  4200.6 1788.56  4238.8 1788.19    4343 1788.31
  4447.5 1786.36  4457.9  1786.5  4507.8 1785.94  4562.4 1786.14  4572.8 1786.06
  4584.2 1785.54  4644.9 1784.71  4769.3 1784.22  4858.7 1783.96  4897.9 1783.92
  4948.9 1784.48  4988.2  1783.2  4988.5  1782.7    4992  1782.7  4992.2  1783.2
  5004.3 1783.48    5076 1783.39    5104 1784.45  5134.6 1784.52    5364 1785.38
    5392 1785.45  5449.6 1785.88  5495.4 1786.73  5561.9 1786.59  5675.8 1787.77
#Mann= 7 ,-1 , 0
  4060.3    .045       0  4769.3     .07       0  4858.7    .045       0
  4897.9     .07       0  5134.6    .045       0    5364     .07       0
    5392    .045       0
Bank Sta=4988.2,4992.2
XS Rating Curve= 0 ,0
Exp/Cntr=0.3,0.1

Type RM Length L Ch R = 1 ,17725   ,331,331,331
BEGIN DESCRIPTION:
Elm 01 33 17725.44
END DESCRIPTION:
XS GIS Cut Line= 5
      1546533.06      6841934.99      1546880.99      6841262.27
      1546911.22      6841194.55      1546887.59      6841145.56
      1546713.31      6840474.96
#Sta/Elev= 30
  4163.5 1788.45  4246.6 1788.35    4306 1787.16    4433 1787.04  4509.4 1785.95
    4601 1786.06  4662.7 1784.36  4731.6 1783.94    4774 1783.79  4859.8 1783.38
  4911.9 1784.26  4971.2 1783.42  4988.9 1782.52  5019.9 1782.82    5078 1782.51
  5078.3 1782.01  5081.8 1782.01    5082 1782.51  5093.3 1782.59  5110.3  1783.7
  5124.4 1784.03  5167.3 1783.51  5213.3 1783.45    5291 1784.11  5335.4 1783.82
  5381.1 1784.34  5579.6 1785.58    5647 1786.55  5734.5 1786.91  5742.3 1786.97
#Mann= 7 ,-1 , 0
  4163.5    .045       0  4731.6     .07       0    4774    .045       0
  4911.9     .07       0  5167.3    .045       0  5381.1    .035       0
  5734.5     .07       0
Bank Sta=5078,5082
XS Rating Curve= 0 ,0
Exp/Cntr=0.3,0.1

Type RM Length L Ch R = 1 ,17394   ,403,403,403
BEGIN DESCRIPTION:
Elm 01 33 17393.82
END DESCRIPTION:
XS GIS Cut Line= 6
      1546938.74      6841802.53      1547205.71      6841261.14
      1547240.04      6841221.67      1547216.68      6841185.72
      1547030.83        6840673.      1546811.56      6840178.09
#Sta/Elev= 30
  4346.9 1786.15  4420.8 1786.43    4456 1785.46  4463.6 1785.74  4512.9 1784.96
  4555.7 1784.88  4676.3 1783.22  4725.6 1783.33  4799.9 1782.74  4888.4 1782.39
  4924.1 1782.68  4967.4  1781.4  5014.8 1781.24  5021.2 1781.06  5021.4 1780.56
  5024.9 1780.56  5025.2 1781.06  5080.5 1781.53  5116.8 1782.78  5166.4 1782.46
  5218.5 1782.72  5261.7 1783.05  5355.4 1782.64  5568.8 1784.15  5815.2 1785.54
  5878.7 1786.68  5929.9  1786.5  6041.3 1787.83  6097.9 1787.46  6132.4  1787.9
#Mann= 10 ,-1 , 0
  4346.9    .045       0  4799.9     .07       0  4967.4    .035       0
  5014.8     .07       0  5021.2     .07       0  5025.2     .07       0
  5166.4    .045       0  5218.5     .07       0  5568.8    .035       0
  5929.9     .07       0
Bank Sta=5021.2,5025.2
XS Rating Curve= 0 ,0
Exp/Cntr=0.3,0.1

Type RM Length L Ch R = 1 ,16991   ,323,323,323
BEGIN DESCRIPTION:
Elm 01 33 16991.354
END DESCRIPTION:
XS GIS Cut Line= 4
      1547651.41      6842030.34      1547770.03      6841390.07
      1547280.45      6840598.41       1546983.8      6839566.37
#Sta/Elev= 30
  4086.4 1782.12  4289.6 1780.96  4409.6 1783.71  4559.6 1781.09  4961.6  1781.4
  4982.9 1779.16  5006.3 1778.85  5006.8 1778.35  5014.5 1778.85  5040.8 1781.82
  5303.2 1780.61  5471.5 1781.67    5763 1782.51  6034.4 1779.58  6175.3 1783.83
  6245.7 1784.98  6278.3 1783.98  6296.9 1785.06  6305.7 1784.05  6310.9 1785.08
  6359.7  1785.8  6485.3 1786.55  6511.8 1788.28    6517 1787.37  6544.4 1788.73
  6569.1 1788.11  6609.6 1789.32  6614.8 1790.48  6652.8 1789.52  6742.2 1792.14
#Mann= 4 ,-1 , 0
  4086.4    .035       0  5006.3     .07       0  5014.5    .035       0
  5471.5     .07       0
Bank Sta=5006.3,5014.5
XS Rating Curve= 0 ,0
Exp/Cntr=0.3,0.1