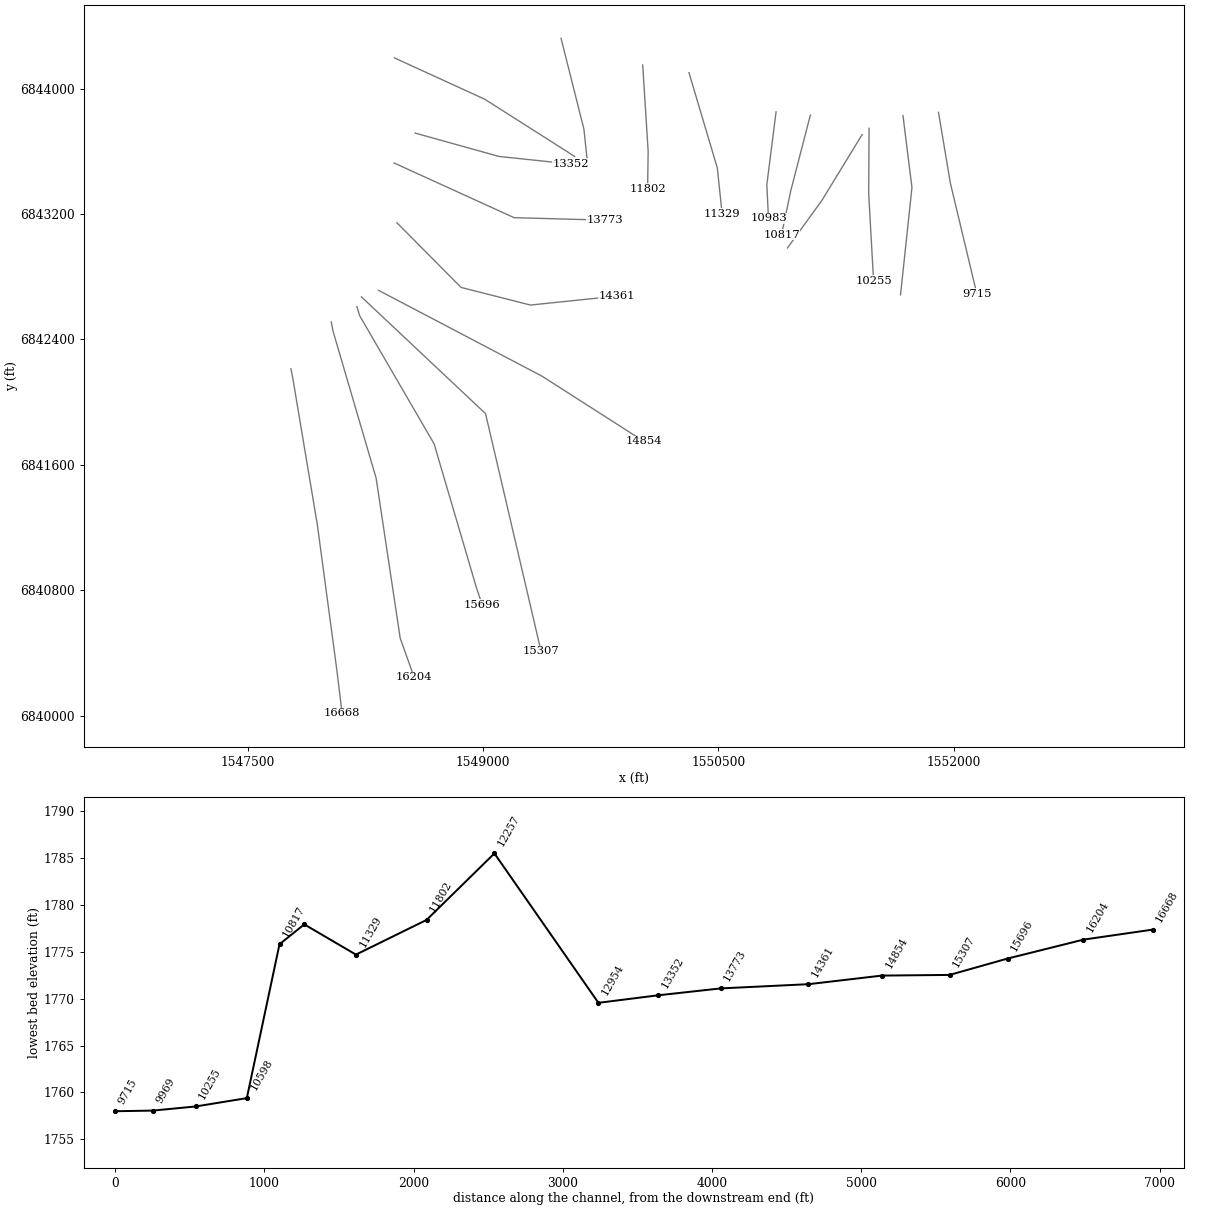
HEC-RAS study Elm 01 33.prj: Elm 01 33 Base Level Engineering

--- Elm 01 33.g01 (geometry) --- (continued)

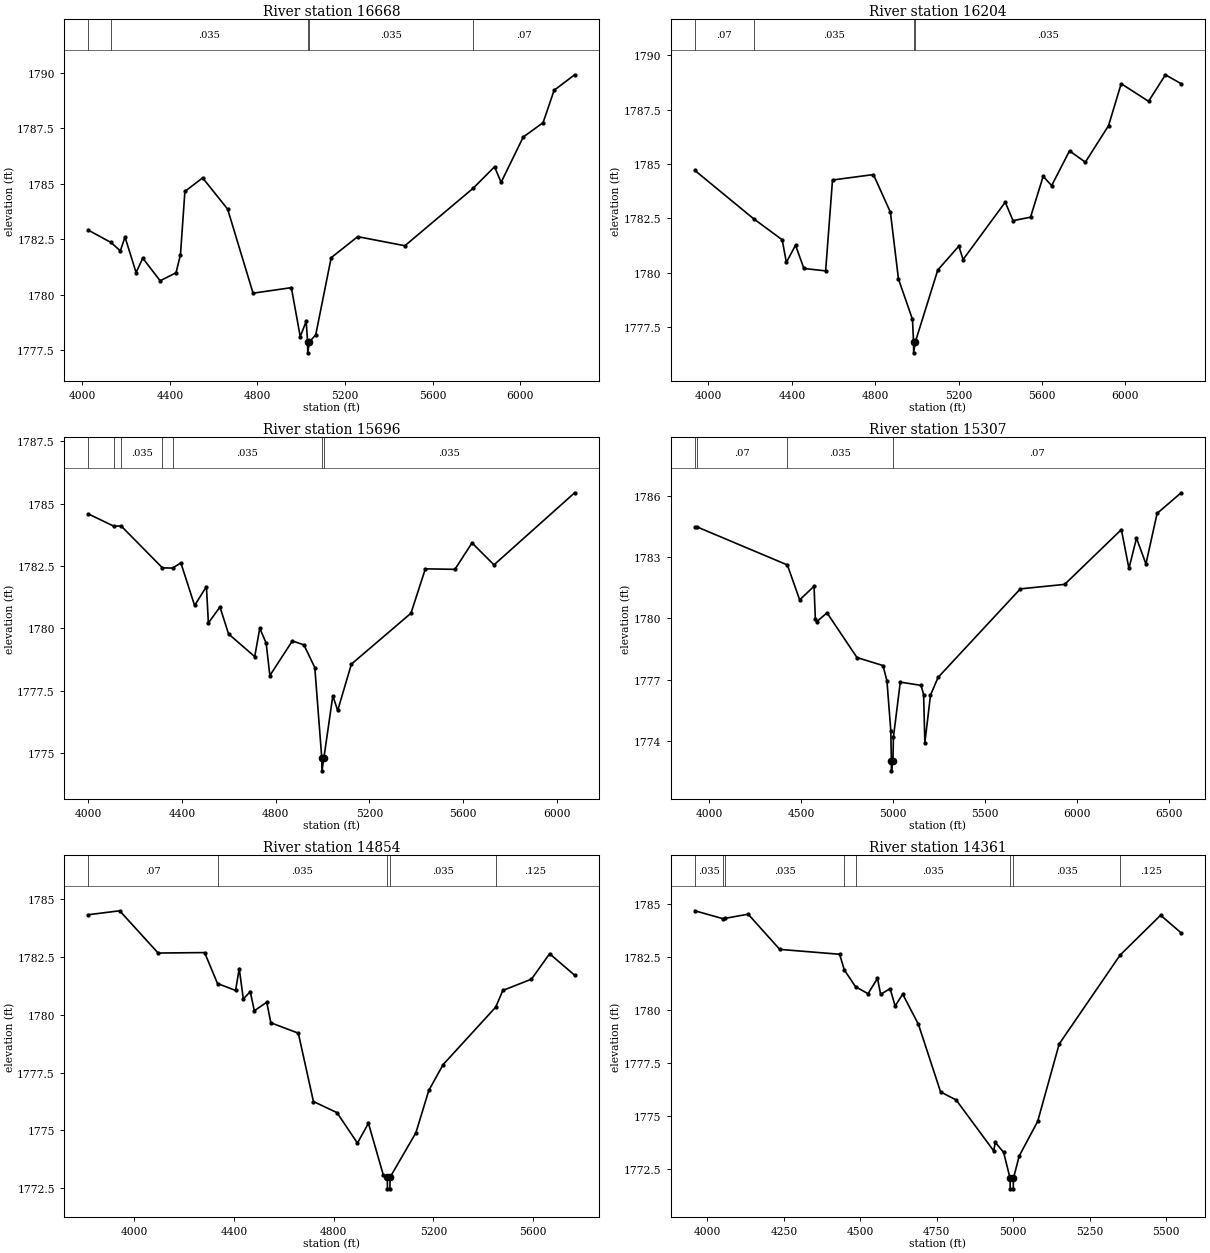
Type RM Length L Ch R = 1 ,16668   ,464,464,464
BEGIN DESCRIPTION:
Elm 01 33 16667.946
END DESCRIPTION:
XS GIS Cut Line= 5
      1547773.52      6842212.67      1547786.41      6842146.31
      1547941.91       6841218.2      1548066.16      6840292.32
      1548099.93      6840014.59
#Sta/Elev= 30
  4027.1 1782.91  4129.8 1782.36    4173 1781.98  4194.4  1782.6  4245.1    1781
  4275.5 1781.65    4355 1780.63  4427.6 1780.99  4447.9 1781.81  4468.1 1784.66
  4549.3 1785.27  4663.5 1783.86  4779.8 1780.07  4954.8 1780.32  4995.4 1778.11
  5022.5  1778.8  5029.1 1777.88  5029.6 1777.38  5037.5 1777.88  5066.2 1778.19
  5136.8 1781.67  5257.9 1782.62  5473.7 1782.21  5786.6 1784.81  5883.5 1785.77
  5913.7 1785.07  6014.6 1787.11  6105.4 1787.76  6155.9 1789.22  6249.7 1789.92
#Mann= 5 ,-1 , 0
  4027.1     .07       0  4129.8    .035       0  5029.1     .07       0
  5037.5    .035       0  5786.6     .07       0
Bank Sta=5029.1,5037.5
XS Rating Curve= 0 ,0
Exp/Cntr=0.3,0.1

Type RM Length L Ch R = 1 ,16204   ,508,508,508
BEGIN DESCRIPTION:
Elm 01 33 16204.24
END DESCRIPTION:
XS GIS Cut Line= 5
      1548030.72      6842511.22        1548042.      6842452.71
      1548316.91      6841515.07      1548470.45       6840494.2
      1548558.87      6840246.14
#Sta/Elev= 30
    3935  1784.7  4216.4 1782.48  4353.8 1781.51  4373.9 1780.47  4417.8 1781.26
    4458 1780.19  4562.2 1780.08  4595.2 1784.26  4791.5 1784.51  4872.9 1782.78
  4911.5 1779.71  4978.8 1777.85  4983.9 1776.81  4984.4 1776.31  4992.4 1776.81
  5100.2 1780.12  5201.3 1781.22  5221.5  1780.6  5423.8 1783.24  5461.2 1782.39
  5545.1 1782.55  5605.8 1784.43  5646.3    1784  5732.1  1785.6  5808.1 1785.08
  5919.3 1786.76    5980 1788.69  6111.4 1787.88  6192.3  1789.1  6267.4 1788.69
#Mann= 4 ,-1 , 0
    3935     .07       0  4216.4    .035       0  4983.9     .07       0
  4992.4    .035       0
Bank Sta=4983.9,4992.4
XS Rating Curve= 0 ,0
Exp/Cntr=0.3,0.1

Type RM Length L Ch R = 1 ,15696   ,389,389,389
BEGIN DESCRIPTION:
Elm 01 33 15695.6
END DESCRIPTION:
XS GIS Cut Line= 5
      1548194.08      6842609.08      1548212.02      6842551.06
       1548686.7      6841733.82      1548955.77      6840819.89
      1548992.75      6840709.04
#Sta/Elev= 30
  4000.9 1784.59  4109.6  1784.1  4140.6 1784.11  4316.7 1782.43  4360.6 1782.42
  4395.4 1782.63  4454.2 1780.92  4504.6 1781.68    4513 1780.22  4562.4 1780.86
  4599.1 1779.78  4710.8 1778.87  4732.3 1780.01  4759.6 1779.41  4775.4 1778.11
  4871.4  1779.5  4920.9 1779.34  4967.2 1778.43  4997.1 1774.79  4997.6 1774.29
  5005.7 1774.79  5044.1  1777.3  5064.9 1776.71  5123.4 1778.57  5377.7 1780.61
  5439.1 1782.39  5565.3 1782.37  5638.3 1783.43  5732.1 1782.55  6076.3 1785.44
#Mann= 7 ,-1 , 0
  4000.9    .035       0  4109.6     .07       0  4140.6    .035       0
  4316.7     .07       0  4360.6    .035       0  4997.1     .07       0
  5005.7    .035       0
Bank Sta=4997.1,5005.7
XS Rating Curve= 0 ,0
Exp/Cntr=0.3,0.1

Type RM Length L Ch R = 1 ,15307   ,453,453,453
BEGIN DESCRIPTION:
Elm 01 33 15306.7
END DESCRIPTION:
XS GIS Cut Line= 3
      1548223.18       6842671.3      1549014.82      6841926.53
      1549368.75      6840411.94
#Sta/Elev= 30
  3923.8 1784.46  3935.6 1784.47  4426.4 1782.61  4493.3  1780.9  4571.4 1781.57
  4578.3 1779.99  4585.3 1779.83  4641.8 1780.27  4804.8 1778.08    4946 1777.69
  4967.5 1776.94  4988.5 1774.51  4991.5 1773.04    4992 1772.54  5000.2 1773.04
  5002.7 1774.18    5040 1776.88    5153 1776.72  5166.8 1776.27  5173.5 1773.91
  5204.2 1776.24  5245.4 1777.11  5692.4 1781.44  5933.4 1781.66  6241.5 1784.34
  6282.6 1782.44  6323.7 1783.92    6375 1782.66  6435.6 1785.13  6566.1 1786.14
#Mann= 4 ,-1 , 0
  3923.8    .035       0  3935.6     .07       0  4426.4    .035       0
  5000.2     .07       0
Bank Sta=4991.5,5000.2
XS Rating Curve= 0 ,0
Exp/Cntr=0.3,0.1

Type RM Length L Ch R = 1 ,14854   ,493,493,493
BEGIN DESCRIPTION:
Elm 01 33 14853.88
END DESCRIPTION:
XS GIS Cut Line= 3
      1548332.49      6842713.01       1549374.2      6842166.11
      1550025.24      6841749.45
#Sta/Elev= 30
  3816.4 1784.34  3941.7 1784.51    4096 1782.68  4282.3  1782.7    4334 1781.36
  4406.5 1781.06  4421.1 1782.01  4437.5 1780.69  4465.2 1781.01  4481.6 1780.18
  4531.4 1780.55  4547.8 1779.66    4658 1779.21  4718.6 1776.25  4813.1 1775.77
    4895 1774.45  4939.1 1775.31  4999.3 1773.05  5014.9 1772.97  5015.4 1772.47
  5025.4 1772.47  5025.9 1772.97  5129.5  1774.9  5181.1 1776.73  5238.6 1777.85
  5449.6 1780.34  5477.9 1781.06  5592.9 1781.55  5665.6 1782.65  5765.9 1781.72
#Mann= 5 ,-1 , 0
  3816.4     .07       0    4334    .035       0  5014.9     .07       0
  5025.9    .035       0  5449.6    .125       0
Bank Sta=5014.9,5025.9
XS Rating Curve= 0 ,0
Exp/Cntr=0.3,0.1

Type RM Length L Ch R = 1 ,14361   ,588,588,588
BEGIN DESCRIPTION:
Elm 01 33 14361.21
END DESCRIPTION:
XS GIS Cut Line= 4
      1548449.91       6843143.8      1548858.99      6842731.53
      1549301.28      6842619.24      1549851.71      6842676.36
#Sta/Elev= 30
    3959 1784.66  4052.4 1784.28  4056.9  1784.3  4133.3  1784.5  4236.5 1782.84
  4432.5 1782.61  4447.8 1781.87  4484.5 1781.08  4525.4 1780.75  4556.3 1781.47
  4566.6 1780.72  4597.6 1780.99  4614.1 1780.17  4638.8 1780.73  4690.4  1779.3
  4762.7 1776.12  4813.7 1775.74  4936.5 1773.34  4941.7 1773.74    4969 1773.27
    4990 1772.05  4990.5 1771.55  5000.5 1771.55    5001 1772.05    5020  1773.1
  5080.3 1774.73  5150.7 1778.38  5349.9 1782.57  5482.4 1784.45  5549.5 1783.62
#Mann= 8 ,-1 , 0
    3959    .035       0  4052.4     .07       0  4056.9    .035       0
  4447.8     .07       0  4484.5    .035       0    4990     .07       0
    5001    .035       0  5349.9    .125       0
Bank Sta=4990,5001
XS Rating Curve= 0 ,0
Exp/Cntr=0.3,0.1

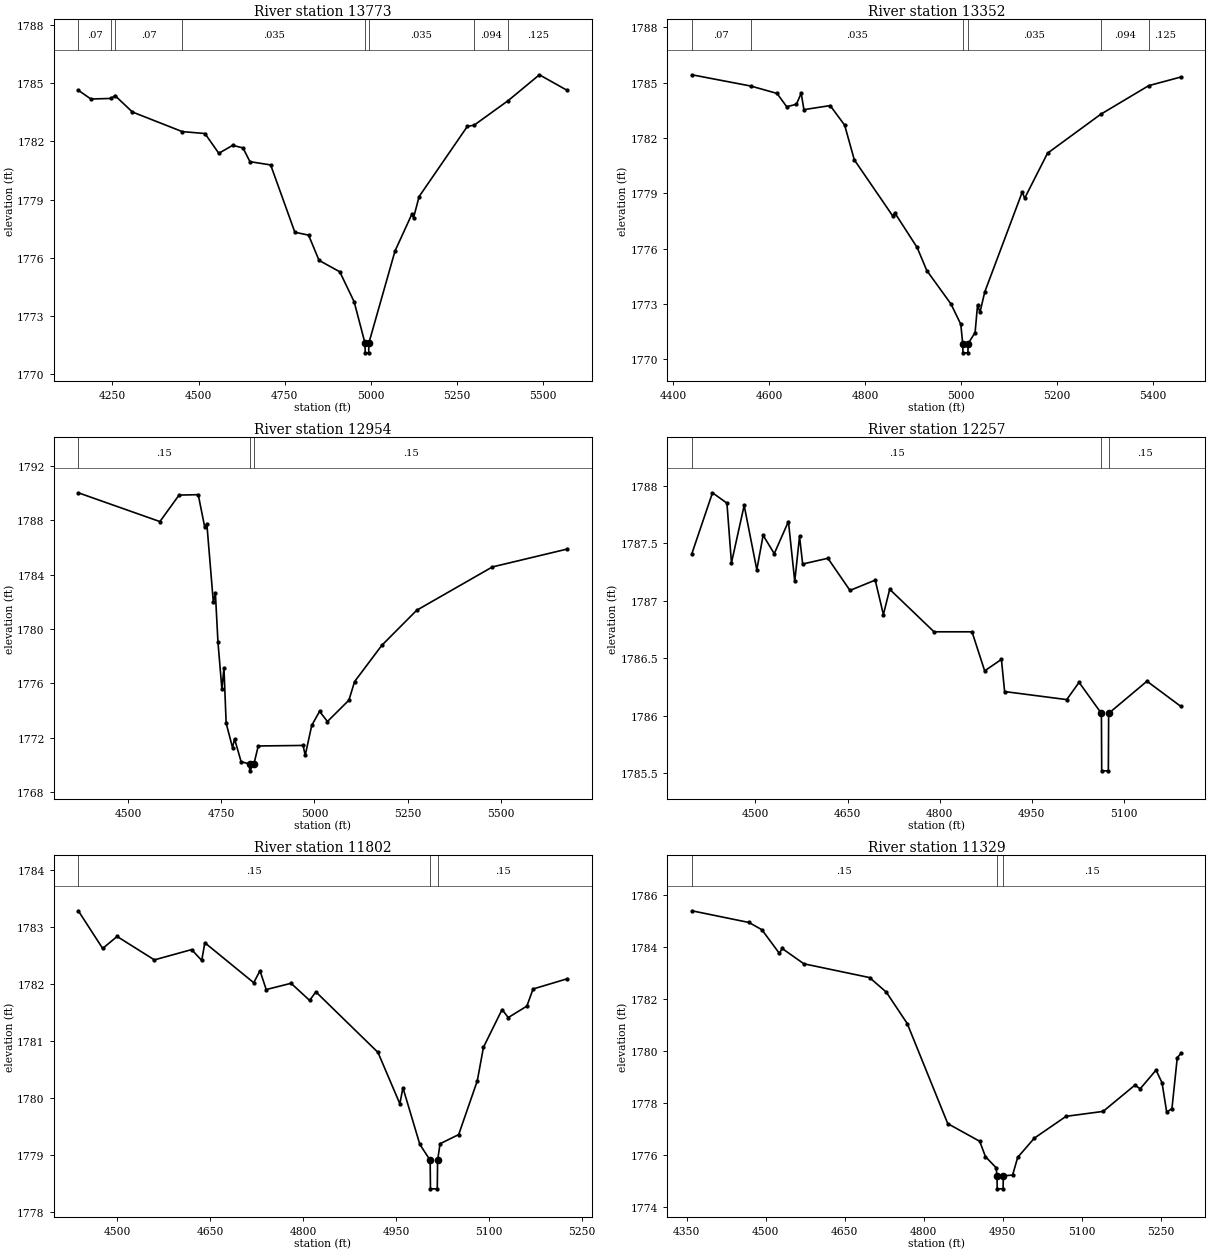
Type RM Length L Ch R = 1 ,13773   ,421,421,421
BEGIN DESCRIPTION:
Elm 01 33 13773.16
END DESCRIPTION:
XS GIS Cut Line= 3
      1548431.58      6843525.43      1549197.11      6843176.53
      1549775.21      6843160.91
#Sta/Elev= 30
  4151.1 1784.64  4187.7 1784.19  4246.3 1784.22  4257.5 1784.37  4308.1 1783.52
  4452.7 1782.51  4518.7 1782.41  4558.9 1781.39    4599  1781.8  4629.1 1781.67
  4649.2 1780.96  4709.4 1780.79  4779.6 1777.32  4819.5 1777.17  4849.8 1775.87
    4910 1775.28  4951.8 1773.73  4983.2  1771.6  4983.7  1771.1  4993.9  1771.1
  4994.4  1771.6  5070.3 1776.35  5119.2 1778.25  5124.2 1778.07  5140.3 1779.16
  5280.4 1782.78  5299.9 1782.84    5399 1784.11  5489.4 1785.44  5570.7 1784.63
#Mann= 8 ,-1 , 0
  4151.1     .07       0  4246.3    .035       0  4257.5     .07       0
  4452.7    .035       0  4983.2     .07       0  4994.4    .035       0
  5299.9    .094       0    5399    .125       0
Bank Sta=4983.2,4994.4
XS Rating Curve= 0 ,0
Exp/Cntr=0.3,0.1

Type RM Length L Ch R = 1 ,13352   ,398,398,398
BEGIN DESCRIPTION:
Elm 01 33 13351.64
END DESCRIPTION:
XS GIS Cut Line= 3
       1548565.9      6843716.19      1549100.76      6843567.16
      1549561.28      6843518.68
#Sta/Elev= 30
  4439.4 1785.43    4562 1784.82  4616.7 1784.42  4636.8  1783.7    4657 1783.83
    4667 1784.43  4672.7 1783.54  4727.4 1783.76  4757.5  1782.7  4777.6 1780.82
  4857.3 1777.79  4862.3 1777.93  4908.4 1776.07  4928.5 1774.82  4978.8 1773.01
  4999.3 1771.91  5003.3 1770.86  5003.8 1770.36  5014.1 1770.36  5014.6 1770.86
  5029.1 1771.46  5034.2 1772.96  5039.2 1772.55  5049.2 1773.66  5127.2 1779.07
  5132.3 1778.74  5179.9 1781.18  5290.7 1783.29  5390.5 1784.84  5457.7 1785.31
#Mann= 6 ,-1 , 0
  4439.4     .07       0    4562    .035       0  5003.3     .07       0
  5014.6    .035       0  5290.7    .094       0  5390.5    .125       0
Bank Sta=5003.3,5014.6
XS Rating Curve= 0 ,0
Exp/Cntr=0.3,0.1

Type RM Length L Ch R = 1 ,12954   ,697,697,697
BEGIN DESCRIPTION:
Elm 01 33 12954.19
END DESCRIPTION:
XS GIS Cut Line= 3
      1548434.12      6844195.61      1549010.48      6843931.74
      1549583.42      6843567.14
#Sta/Elev= 30
  4366.1 1790.03  4585.1 1787.91  4636.6 1789.86  4688.1 1789.89  4705.6 1787.48
  4711.1 1787.76  4728.6 1781.98  4734.1 1782.64    4741 1779.04  4751.6 1775.57
  4757.1 1777.14    4763 1773.07  4780.1 1771.27  4785.6 1771.91  4803.1 1770.24
  4825.7 1770.06  4826.2 1769.56  4837.5 1770.06  4849.2 1771.39  4969.7 1771.43
  4975.2 1770.69  4992.7  1772.9  5013.8 1773.94  5034.9 1773.19  5092.5 1774.76
  5107.8 1776.13  5180.6 1778.79  5274.5 1781.38  5477.7 1784.57  5679.1 1785.89
#Mann= 3 ,-1 , 0
  4366.1     .15       0  4825.7     .05       0  4837.5     .15       0
Bank Sta=4825.7,4837.5
XS Rating Curve= 0 ,0
Exp/Cntr=0.3,0.1

Type RM Length L Ch R = 1 ,12257   ,455,455,455
BEGIN DESCRIPTION:
Elm 01 33 12257.32
END DESCRIPTION:
XS GIS Cut Line= 3
       1549496.6      6844320.58      1549642.43      6843740.77
      1549663.25      6843542.93
#Sta/Elev= 30
  4396.4 1787.41    4430 1787.94  4453.5 1787.85  4460.9 1787.33  4481.6 1787.83
  4502.2 1787.27  4512.5 1787.57  4530.6 1787.41  4553.7 1787.69    4564 1787.17
  4571.8 1787.56  4576.9 1787.32    4618 1787.37    4654 1787.09  4695.1 1787.18
  4708.4 1786.88  4718.7  1787.1  4790.9 1786.73  4852.8 1786.73  4873.4 1786.39
  4900.7 1786.49  4905.9 1786.21  5007.1 1786.14  5027.2 1786.29  5063.6 1786.02
  5064.1 1785.52  5074.9 1785.52  5075.4 1786.02  5137.8  1786.3  5193.2 1786.08
#Mann= 3 ,-1 , 0
  4396.4     .15       0  5063.6     .05       0  5075.4     .15       0
Bank Sta=5063.6,5075.4
XS Rating Curve= 0 ,0
Exp/Cntr=0.3,0.1

Type RM Length L Ch R = 1 ,11802   ,473,473,473
BEGIN DESCRIPTION:
Elm 01 33 11802.47
END DESCRIPTION:
XS GIS Cut Line= 3
      1550017.43      6844150.49      1550052.15      6843598.41
      1550048.68       6843362.6
#Sta/Elev= 30
  4437.3 1783.28  4476.6 1782.62  4499.9 1782.83    4560 1782.42  4620.1  1782.6
  4636.4 1782.41  4641.4 1782.72  4720.3 1782.02  4730.4 1782.23  4740.4  1781.9
  4780.5 1782.01  4810.5 1781.71  4820.5 1781.86  4920.7  1780.8    4956  1779.9
    4961 1780.18  4988.2 1779.19  5004.9 1778.91  5005.4 1778.41  5016.4 1778.41
  5016.9 1778.91  5020.9  1779.2  5050.9 1779.36  5080.9  1780.3  5090.9 1780.89
  5120.9 1781.55  5130.9 1781.41  5160.9 1781.61  5170.9 1781.91  5226.3 1782.09
#Mann= 3 ,-1 , 0
  4437.3     .15       0  5004.9     .05       0  5016.9     .15       0
Bank Sta=5004.9,5016.9
XS Rating Curve= 0 ,0
Exp/Cntr=0.3,0.1

Type RM Length L Ch R = 1 ,11329   ,346,346,346
BEGIN DESCRIPTION:
Elm 01 33 11329.49
END DESCRIPTION:
XS GIS Cut Line= 3
      1550312.56      6844101.91      1550493.12      6843494.24
      1550524.17      6843201.01
#Sta/Elev= 30
  4359.6 1785.41    4468 1784.96  4492.6 1784.68  4525.8 1783.77    4531 1783.96
  4572.3 1783.37    4697 1782.84  4728.8 1782.28  4768.6 1781.07  4845.5 1777.22
  4906.2 1776.54  4917.1 1775.95  4937.5 1775.52    4939 1775.21  4939.5 1774.71
  4950.6 1774.71  4951.1 1775.21  4968.7 1775.24  4978.3 1775.92  5009.9 1776.66
  5070.2  1777.5  5140.6 1777.69  5200.9  1778.7    5211 1778.56  5241.1 1779.28
  5252.5 1778.79  5261.3 1777.66  5271.3  1777.8  5281.4 1779.76  5288.4 1779.92
#Mann= 3 ,-1 , 0
  4359.6     .15       0    4939     .05       0  4951.1     .15       0
Bank Sta=4939,4951.1
XS Rating Curve= 0 ,0
Exp/Cntr=0.3,0.1

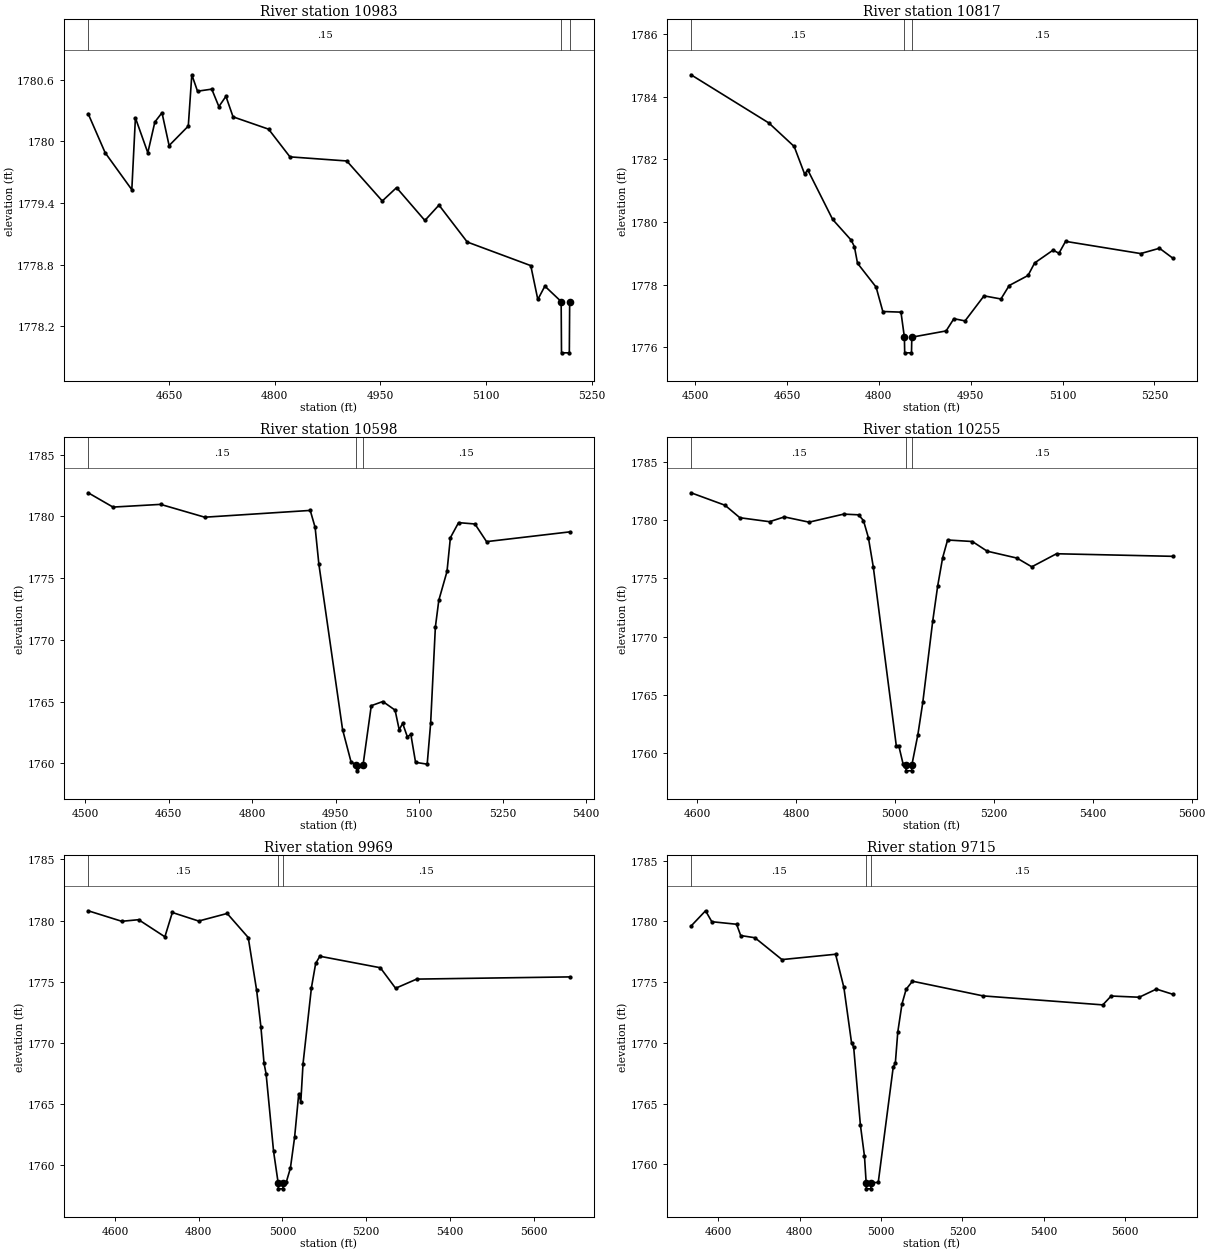
Type RM Length L Ch R = 1 ,10983   ,166,166,166
BEGIN DESCRIPTION:
Elm 01 33 10982.9
END DESCRIPTION:
XS GIS Cut Line= 3
      1550868.12      6843851.88      1550809.09       6843386.6
       1550819.6      6843172.87
#Sta/Elev= 30
  4535.5 1780.27  4559.6 1779.89  4597.4 1779.53  4602.5 1780.23  4620.1 1779.89
  4630.1 1780.19  4640.2 1780.28  4650.3 1779.96  4677.5 1780.15  4682.5 1780.65
  4690.6 1780.49  4710.8 1780.51  4720.9 1780.34  4730.9 1780.44    4741 1780.24
  4791.4 1780.12  4821.7 1779.85  4902.3 1779.81  4952.7 1779.42  4972.9 1779.55
  5013.1 1779.23  5033.1 1779.38  5073.2 1779.02  5163.3 1778.79  5173.3 1778.46
  5183.3 1778.59  5206.4 1778.44  5206.9 1777.94    5218 1777.94  5218.5 1778.44
#Mann= 3 ,-1 , 0
  4535.5     .15       0  5206.4     .05       0  5218.5     .15       0
Bank Sta=5206.4,5218.5
XS Rating Curve= 0 ,0
Exp/Cntr=0.3,0.1

Type RM Length L Ch R = 1 ,10817   ,219,219,219
BEGIN DESCRIPTION:
Elm 01 33 10816.75
END DESCRIPTION:
XS GIS Cut Line= 3
      1551086.87      6843831.06      1550961.87      6843348.41
      1550902.83      6843067.11
#Sta/Elev= 30
  4493.5  1784.7  4620.6 1783.16  4661.9 1782.41  4678.9 1781.53  4684.1 1781.66
  4724.7 1780.08  4754.9 1779.42  4760.2 1779.21  4765.3 1778.68  4795.6 1777.92
  4806.6 1777.14  4836.2 1777.12  4841.8 1776.32  4842.3 1775.82  4853.4 1775.82
  4853.9 1776.32  4909.9 1776.52  4922.6 1776.91  4940.8 1776.84  4971.8 1777.64
  4999.4 1777.54  5012.9 1777.97  5043.6 1778.29  5054.4 1778.69  5084.5  1779.1
  5094.1    1779  5104.9 1779.38  5227.5 1778.99  5258.2 1779.16  5279.5 1778.85
#Mann= 3 ,-1 , 0
  4493.5     .15       0  4841.8     .05       0  4853.9     .15       0
Bank Sta=4841.8,4853.9
XS Rating Curve= 0 ,0
Exp/Cntr=0.3,0.1

Type RM Length L Ch R = 1 ,10598   ,343,343,343
BEGIN DESCRIPTION:
Elm 01 33 10598.38
END DESCRIPTION:
XS GIS Cut Line= 3
      1551416.71      6843706.01      1551159.79      6843285.91
      1550941.05      6842983.83
#Sta/Elev= 30
  4505.3 1781.92  4549.9 1780.76  4635.5 1780.98  4714.8 1779.94  4904.4 1780.49
  4913.2 1779.11  4919.9 1776.14  4962.5 1762.73  4977.9 1760.08  4987.3 1759.88
  4987.8 1759.38  4999.4 1759.88  5014.1 1764.66  5034.9    1765  5056.9  1764.3
  5064.3 1762.71  5070.5 1763.23    5079 1762.13  5085.2 1762.34  5093.7 1760.07
  5114.6 1759.92  5120.8 1763.23  5129.3 1771.03  5135.5 1773.21  5150.2 1775.54
  5156.3 1778.28    5171  1779.5  5200.4 1779.39  5221.3 1777.96  5370.7 1778.75
#Mann= 3 ,-1 , 0
  4505.3     .15       0  4987.3     .05       0  4999.4     .15       0
Bank Sta=4987.3,4999.4
XS Rating Curve= 0 ,0
Exp/Cntr=0.3,0.1

Type RM Length L Ch R = 1 ,10255   ,286,286,286
BEGIN DESCRIPTION:
Elm 01 33 10254.78
END DESCRIPTION:
XS GIS Cut Line= 3
      1551461.44      6843746.82      1551458.83      6843330.18
      1551490.04       6842773.7
#Sta/Elev= 30
  4587.3 1782.34  4656.1 1781.27  4686.1  1780.2  4746.1 1779.86  4776.1 1780.27
  4826.1 1779.82  4896.1 1780.51  4926.1 1780.45  4936.1 1779.96  4946.1 1778.49
  4956.1 1775.95  5002.5 1760.65  5007.5 1760.65  5016.1 1759.11  5021.9 1758.99
  5022.4 1758.49  5033.5 1758.49    5034 1758.99  5046.2  1761.6  5056.2 1764.38
  5076.2 1771.33  5086.3 1774.36  5096.3 1776.77  5106.3 1778.29  5156.4 1778.16
  5186.4 1777.33  5246.5 1776.74  5276.6 1775.99  5326.6 1777.11  5561.3 1776.89
#Mann= 3 ,-1 , 0
  4587.3     .15       0  5021.9     .05       0    5034     .15       0
Bank Sta=5021.9,5034
XS Rating Curve= 0 ,0
Exp/Cntr=0.3,0.1

Type RM Length L Ch R = 1 ,9969    ,254,254,254
BEGIN DESCRIPTION:
Elm 01 33 9969.19
END DESCRIPTION:
XS GIS Cut Line= 3
      1551677.59      6843827.54      1551734.87      6843369.24
      1551661.96      6842684.37
#Sta/Elev= 30
  4535.8  1780.8    4616 1779.94  4656.3 1780.07  4719.1 1778.67  4736.9 1780.66
  4799.8 1779.96  4867.9 1780.58  4918.3 1778.61  4938.4 1774.28  4948.5 1771.32
    4956 1768.33    4961 1767.45  4978.8 1761.12  4989.7 1758.55  4990.2 1758.05
  5001.3 1758.05  5001.8 1758.55    5009 1758.58    5019 1759.74  5029.1 1762.27
  5038.9 1765.81  5043.9 1765.16  5049.2 1768.28  5069.3 1774.51  5079.4 1776.49
  5089.4 1777.08  5233.9 1776.14  5270.4 1774.46  5320.7 1775.21  5686.4 1775.39
#Mann= 3 ,-1 , 0
  4535.8     .15       0  4989.7     .05       0  5001.8     .15       0
Bank Sta=4989.7,5001.8
XS Rating Curve= 0 ,0
Exp/Cntr=0.3,0.1

Type RM Length L Ch R = 1 ,9715    ,223,223,223
BEGIN DESCRIPTION:
Elm 01 33 9715.48
END DESCRIPTION:
XS GIS Cut Line= 3
      1551904.14      6843848.44      1551979.67      6843397.89
      1552148.52      6842691.32
#Sta/Elev= 30
    4533 1779.62  4568.7 1780.88  4584.1 1779.98    4645 1779.77  4655.1 1778.84
    4690 1778.66  4756.5 1776.86  4888.3  1777.3  4908.6 1774.57  4927.6 1769.98
  4932.7 1769.65  4949.2 1763.25  4959.3 1760.65  4963.4 1758.48  4963.9 1757.98
    4975 1757.98  4975.5 1758.48  4993.1 1758.51    5030 1768.03  5035.1 1768.33
  5041.1 1770.89  5051.4  1773.2  5061.7 1774.42  5077.2 1775.08  5250.7 1773.87
  5544.9 1773.13  5565.5 1773.86  5634.5 1773.76  5676.6 1774.43  5716.3 1774.01
#Mann= 3 ,-1 , 0
    4533     .15       0  4963.4     .05       0  4975.5     .15       0
Bank Sta=4963.4,4975.5
XS Rating Curve= 0 ,0
Exp/Cntr=0.3,0.1