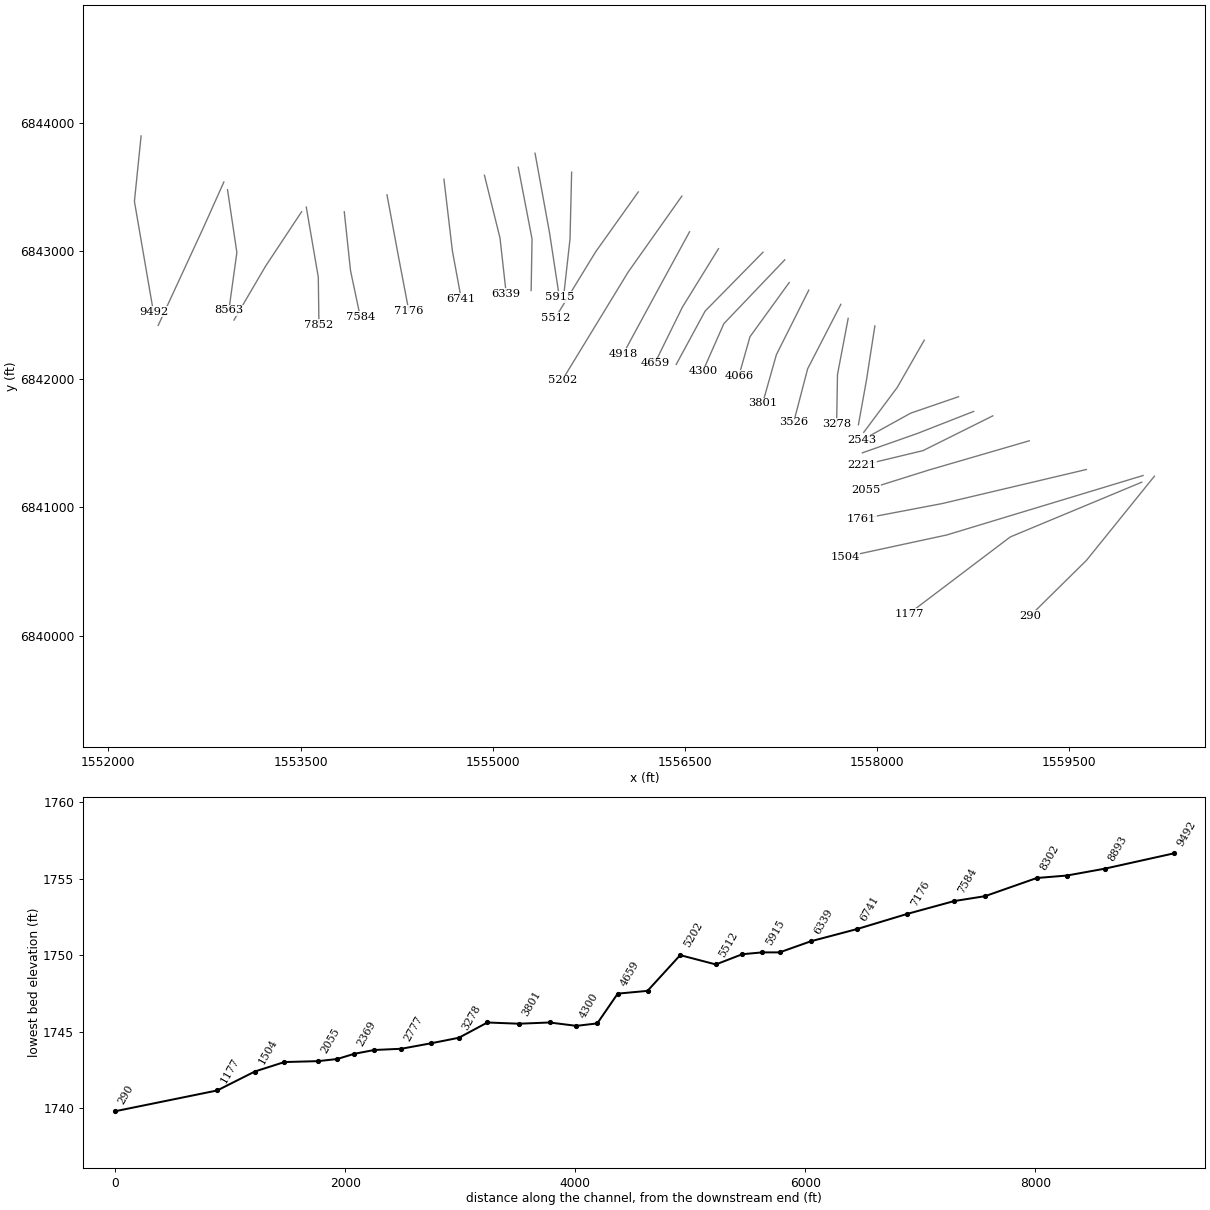
HEC-RAS study Elm 01 33.prj: Elm 01 33 Base Level Engineering

--- Elm 01 33.g01 (geometry) --- (continued)

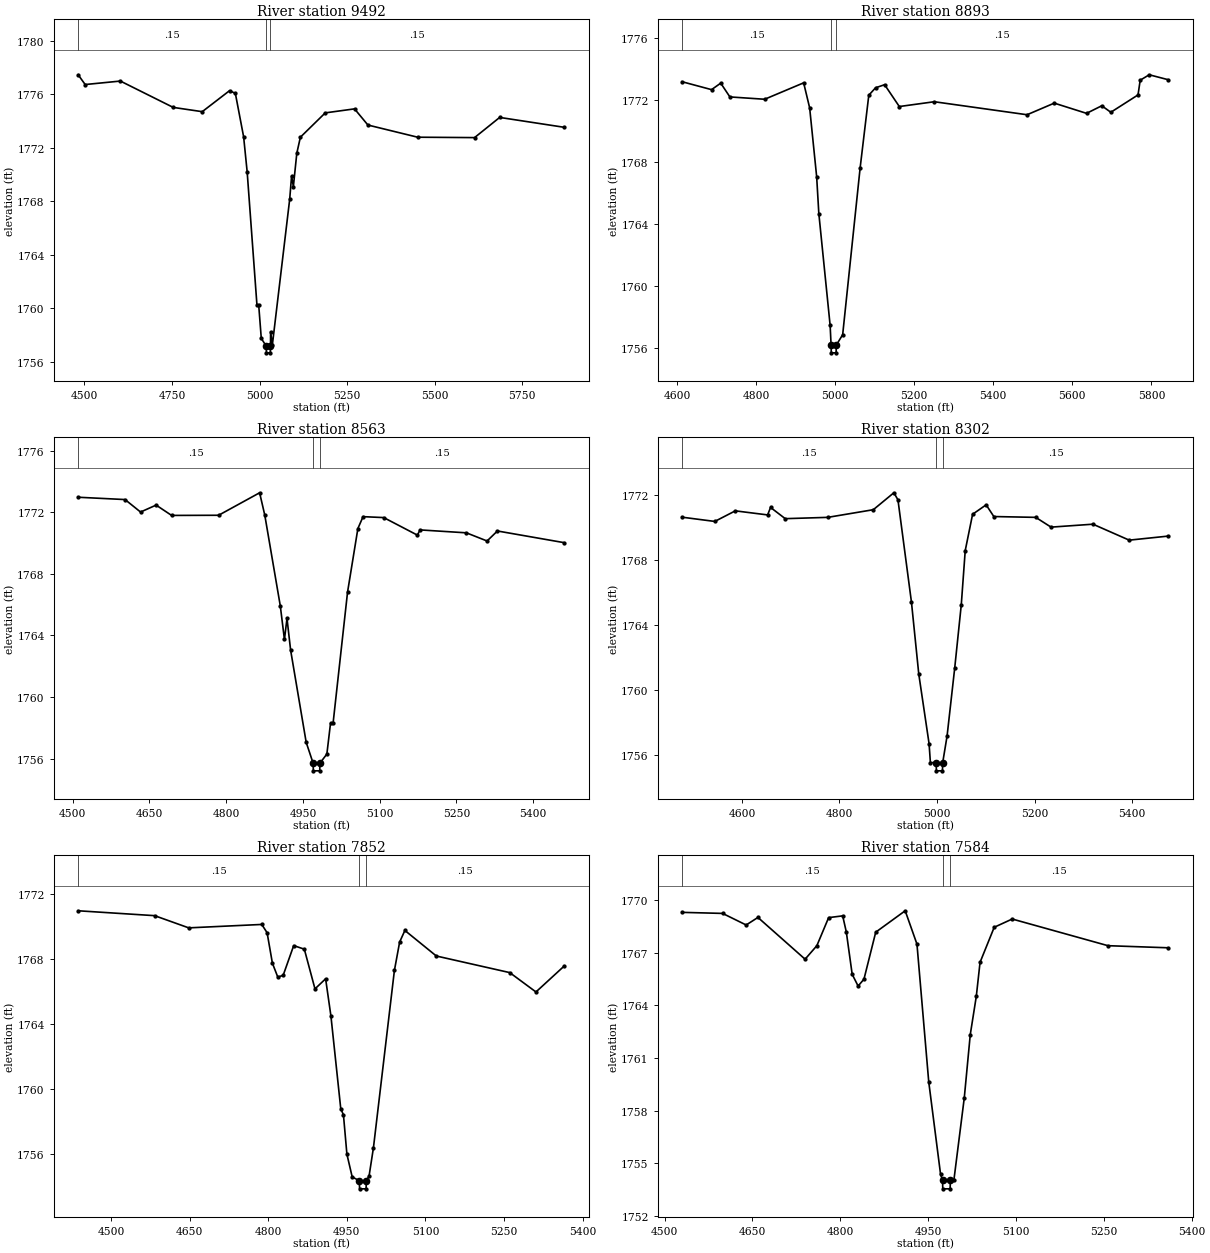
Type RM Length L Ch R = 1 ,9492    ,599,599,599
BEGIN DESCRIPTION:
Elm 01 33 9492.21
END DESCRIPTION:
XS GIS Cut Line= 3
      1552255.71      6843897.86      1552203.62      6843387.47
      1552352.06       6842525.5
#Sta/Elev= 30
  4482.2 1777.46  4502.2 1776.73  4602.7 1776.99  4753.5 1775.02  4836.4  1774.7
  4914.3 1776.27  4930.9 1776.07  4954.5 1772.82  4964.6  1770.2  4992.5 1760.25
  4997.5 1760.25  5004.9 1757.74  5019.1 1757.16  5019.6 1756.66  5030.7 1756.66
  5031.2 1757.16  5031.5 1758.24  5036.6 1757.27    5086 1768.15  5091.4 1769.88
  5096.5  1769.1  5106.3 1771.59  5116.5 1772.79  5187.5 1774.61  5271.1 1774.91
  5309.3  1773.7  5451.3 1772.79  5613.7 1772.76  5685.4 1774.27  5869.9 1773.53
#Mann= 3 ,-1 , 0
  4482.2     .15       0  5019.1     .05       0  5031.2     .15       0
Bank Sta=5019.1,5031.2
XS Rating Curve= 0 ,0
Exp/Cntr=0.3,0.1

Type RM Length L Ch R = 1 ,8893    ,330,330,330
BEGIN DESCRIPTION:
Elm 01 33 8892.54
END DESCRIPTION:
XS GIS Cut Line= 3
      1552901.53      6843538.48      1552742.69      6843184.34
      1552389.27      6842420.35
#Sta/Elev= 30
  4612.9 1773.16  4687.3 1772.65  4710.5 1773.07  4733.7 1772.18  4821.7 1772.03
  4920.3 1773.09  4935.5 1771.47  4953.2 1767.03  4958.7 1764.65  4987.3 1757.43
  4989.7 1756.16  4990.2 1755.66  5002.4 1755.66  5002.9 1756.16    5019 1756.83
  5063.1 1767.58  5085.1 1772.29  5102.2 1772.77  5125.1 1772.97  5162.3 1771.56
  5250.8 1771.87  5485.5 1771.03  5554.3 1771.78    5636 1771.12  5674.5 1771.61
  5697.4 1771.19  5766.2 1772.31  5771.7 1773.26  5794.6 1773.61  5842.8 1773.29
#Mann= 3 ,-1 , 0
  4612.9     .15       0  4989.7     .05       0  5002.9     .15       0
Bank Sta=4989.7,5002.9
XS Rating Curve= 0 ,0
Exp/Cntr=0.3,0.1

Type RM Length L Ch R = 1 ,8563    ,261,261,261
BEGIN DESCRIPTION:
Elm 01 33 8562.59
END DESCRIPTION:
XS GIS Cut Line= 3
      1552930.19       6843478.6       1553003.1      6842989.03
       1552940.6      6842538.52
#Sta/Elev= 30
  4510.9 1772.97  4602.5 1772.82  4632.8 1772.01  4663.2 1772.46  4693.5 1771.79
  4785.3  1771.8  4865.4 1773.26  4875.5 1771.81  4905.8 1765.92  4913.9 1763.74
  4918.9  1765.1    4926 1763.04  4956.4 1757.06  4969.9 1755.71  4970.4 1755.21
  4982.8 1755.21  4983.3 1755.71  4996.8  1756.3  5003.9 1758.29  5008.9 1758.29
  5037.2 1766.81  5057.4 1770.94  5067.5 1771.71  5107.9 1771.65  5173.7 1770.51
  5178.8 1770.85  5269.4 1770.66  5309.8 1770.13    5330 1770.78  5460.7 1770.02
#Mann= 3 ,-1 , 0
  4510.9     .15       0  4969.9     .05       0  4983.3     .15       0
Bank Sta=4969.9,4983.3
XS Rating Curve= 0 ,0
Exp/Cntr=0.3,0.1

Type RM Length L Ch R = 1 ,8302    ,450,450,450
BEGIN DESCRIPTION:
Elm 01 33 8302.13
END DESCRIPTION:
XS GIS Cut Line= 3
      1553508.31      6843306.74      1553227.06      6842882.26
      1552980.61      6842461.99
#Sta/Elev= 30
  4477.5 1770.63  4544.4 1770.37  4586.5 1771.02  4652.7 1770.77  4658.7 1771.23
  4688.8 1770.54  4775.9 1770.62  4869.3 1771.09  4911.4 1772.13  4919.8  1771.7
  4947.5 1765.41  4962.5 1760.99  4983.6 1756.72  4986.3 1755.56  4998.1 1755.55
  4998.6 1755.05    5011 1755.05  5011.5 1755.55  5020.5 1757.19  5036.2 1761.38
  5049.6 1765.25  5057.7 1768.58  5072.8 1770.81  5100.6 1771.39  5116.3 1770.67
  5202.2 1770.62  5233.6 1770.02  5319.5  1770.2  5393.8 1769.22  5473.9 1769.47
#Mann= 3 ,-1 , 0
  4477.5     .15       0  4998.1     .05       0  5011.5     .15       0
Bank Sta=4998.1,5011.5
XS Rating Curve= 0 ,0
Exp/Cntr=0.3,0.1

Type RM Length L Ch R = 1 ,7852    ,268,268,268
BEGIN DESCRIPTION:
Elm 01 33 7852.32
END DESCRIPTION:
XS GIS Cut Line= 3
      1553544.77       6843343.2      1553638.52      6842796.32
      1553643.73      6842423.92
#Sta/Elev= 30
  4437.5 1770.95  4583.3 1770.65  4648.4  1769.9  4787.7 1770.11  4797.9  1769.6
    4808 1767.73  4818.2 1766.88  4828.5 1766.98  4848.6 1768.81  4868.9 1768.59
  4889.2 1766.15  4909.5 1766.77  4919.6 1764.49  4938.4 1758.78  4943.5 1758.41
  4950.1 1755.99  4960.2 1754.59  4973.8 1754.36  4974.3 1753.86  4986.7 1753.86
  4987.2 1754.36  4992.4 1754.65  5000.7 1756.38  5040.7 1767.28  5050.7 1769.03
  5060.7 1769.74  5120.7 1768.17  5260.7 1767.15  5310.7 1765.96  5364.8 1767.56
#Mann= 3 ,-1 , 0
  4437.5     .15       0  4973.8     .05       0  4987.2     .15       0
Bank Sta=4973.8,4987.2
XS Rating Curve= 0 ,0
Exp/Cntr=0.3,0.1

Type RM Length L Ch R = 1 ,7584    ,408,408,408
BEGIN DESCRIPTION:
Elm 01 33 7583.56
END DESCRIPTION:
XS GIS Cut Line= 3
      1553841.22      6843306.69      1553889.82      6842848.41
      1553966.22      6842487.25
#Sta/Elev= 30
    4530  1769.3  4599.1 1769.24  4639.3 1768.58  4659.4 1769.01  4739.9 1766.63
    4760  1767.4  4780.1    1769  4804.1  1769.1  4810.3 1768.18  4820.3 1765.77
  4830.4  1765.1  4840.4 1765.49  4860.5 1768.17  4910.8 1769.39  4930.9 1767.49
    4951 1759.64  4971.2 1754.37  4974.5 1754.04    4975 1753.54  4987.5 1753.54
    4988 1754.04    4994 1754.05  5011.7 1758.73  5021.9 1762.33  5032.2 1764.51
  5038.6 1766.45  5062.8 1768.45  5093.5 1768.92    5257  1767.4    5360 1767.28
#Mann= 3 ,-1 , 0
    4530     .15       0  4974.5     .05       0    4988     .15       0
Bank Sta=4974.5,4988
XS Rating Curve= 0 ,0
Exp/Cntr=0.3,0.1

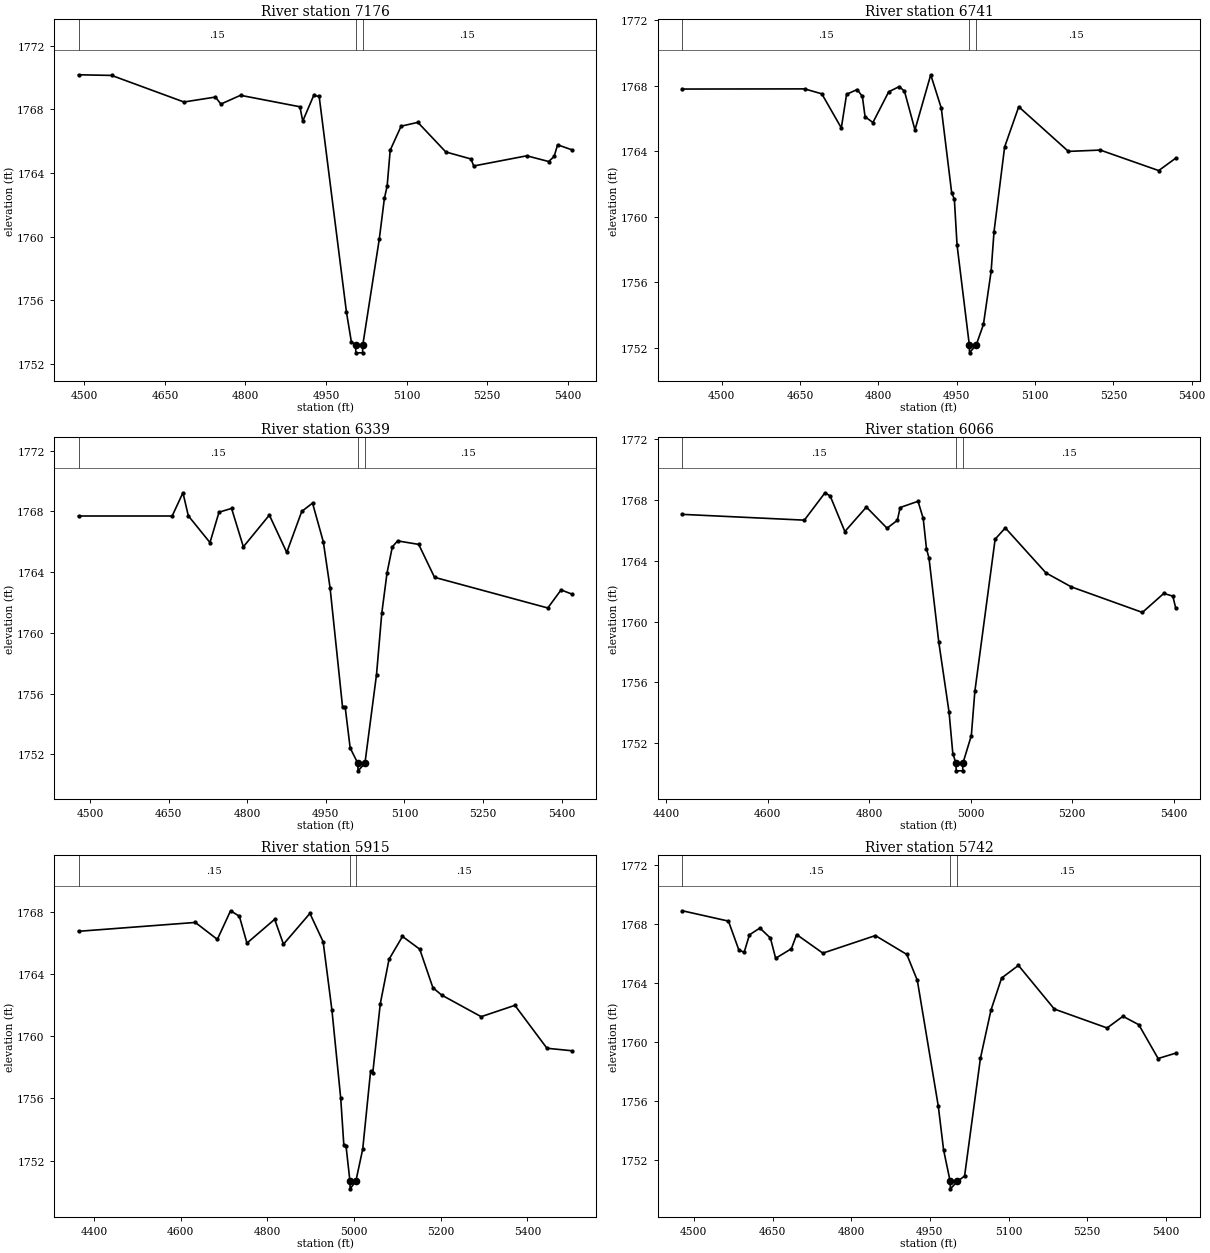
Type RM Length L Ch R = 1 ,7176    ,435,435,435
BEGIN DESCRIPTION:
Elm 01 33 7176.14
END DESCRIPTION:
XS GIS Cut Line= 3
      1554174.55      6843438.68      1554268.29      6842935.21
      1554344.69      6842535.88
#Sta/Elev= 30
    4489 1770.17  4550.7 1770.13  4685.4 1768.46    4744 1768.77  4754.2 1768.33
  4790.8 1768.88  4901.4 1768.16  4906.7 1767.26  4927.1 1768.87  4937.3 1768.81
  4988.1 1755.26  4997.2  1753.4  5005.1  1753.2  5005.6  1752.7  5018.1  1752.7
  5018.6  1753.2  5049.2 1759.83  5058.8 1762.41  5063.9 1763.17  5069.6 1765.43
  5089.9 1766.94  5121.1 1767.18  5173.2 1765.32  5220.1 1764.88  5225.2 1764.44
  5324.1 1765.08  5364.8 1764.72    5375 1765.04  5381.4 1765.77  5407.7 1765.46
#Mann= 3 ,-1 , 0
    4489     .15       0  5005.1     .05       0  5018.6     .15       0
Bank Sta=5005.1,5018.6
XS Rating Curve= 0 ,0
Exp/Cntr=0.3,0.1

Type RM Length L Ch R = 1 ,6741    ,402,402,402
BEGIN DESCRIPTION:
Elm 01 33 6741.19
END DESCRIPTION:
XS GIS Cut Line= 3
      1554618.98      6843560.25      1554684.96      6843001.18
       1554754.4      6842626.21
#Sta/Elev= 30
  4424.8 1767.79  4658.7  1767.8  4691.7  1767.5  4729.1 1765.42  4739.2 1767.47
  4759.4 1767.76  4769.4 1767.34  4774.6  1766.1  4789.6 1765.75  4819.8 1767.62
  4839.9 1767.94    4850 1767.66  4870.1  1765.3  4900.3 1768.66  4920.5 1766.63
  4940.5 1761.44  4945.5 1761.09  4950.7 1758.28  4974.1 1752.21  4974.6 1751.71
  4987.6 1752.21  5001.2 1753.44  5015.9 1756.67  5021.5  1759.1  5041.8 1764.26
  5068.8 1766.71  5163.9 1763.99  5224.9 1764.07  5336.8 1762.82  5369.1 1763.57
#Mann= 3 ,-1 , 0
  4424.8     .15       0  4974.1     .05       0  4987.6     .15       0
Bank Sta=4974.1,4987.6
XS Rating Curve= 0 ,0
Exp/Cntr=0.3,0.1

Type RM Length L Ch R = 1 ,6339    ,273,273,273
BEGIN DESCRIPTION:
Elm 01 33 6339.1
END DESCRIPTION:
XS GIS Cut Line= 3
      1554934.96      6843591.46      1555056.49      6843101.88
       1555105.1      6842667.83
#Sta/Elev= 30
  4478.1  1767.7  4656.8  1767.7  4677.4 1769.23  4687.7 1767.71    4729 1765.95
  4746.2 1767.95  4770.2  1768.2  4792.7 1765.67  4842.3 1767.76  4875.5  1765.3
  4904.1    1768  4924.7 1768.55  4945.3    1766  4958.2 1762.96    4982 1755.11
    4987 1755.11  4996.5 1752.42  5011.1 1751.41  5011.6 1750.91  5024.7 1751.41
  5046.8 1757.25  5056.9 1761.31  5066.9 1763.95    5077 1765.67  5087.1 1766.06
  5127.3 1765.83  5157.5 1763.66  5373.7 1761.64    5399 1762.83  5419.3 1762.56
#Mann= 3 ,-1 , 0
  4478.1     .15       0  5011.1     .05       0  5024.7     .15       0
Bank Sta=5011.1,5024.7
XS Rating Curve= 0 ,0
Exp/Cntr=0.3,0.1

Type RM Length L Ch R = 1 ,6066    ,151,151,151
BEGIN DESCRIPTION:
Elm 01 33 6066.08
END DESCRIPTION:
XS GIS Cut Line= 3
      1555198.85      6843653.97      1555306.49      6843094.93
      1555299.55       6842692.6
#Sta/Elev= 30
  4432.2 1767.05  4672.5 1766.67  4713.2 1768.47  4723.4 1768.26  4752.3 1765.92
  4794.7 1767.53  4835.4 1766.14  4855.8 1766.66  4861.2  1767.5  4896.5 1767.91
  4906.7 1766.78  4913.1 1764.79  4918.1 1764.17  4937.3 1758.66  4957.6 1754.04
    4965 1751.32  4971.2 1750.68  4971.7 1750.18  4984.4 1750.18  4984.9 1750.68
  5001.5  1752.5  5008.4  1755.4  5048.4 1765.42  5068.4 1766.16  5148.5  1763.2
  5198.5 1762.28  5338.5  1760.6  5380.7 1761.85  5398.5 1761.67  5403.9 1760.92
#Mann= 3 ,-1 , 0
  4432.2     .15       0  4971.2     .05       0  4984.9     .15       0
Bank Sta=4971.2,4984.9
XS Rating Curve= 0 ,0
Exp/Cntr=0.3,0.1

Type RM Length L Ch R = 1 ,5915    ,173,173,173
BEGIN DESCRIPTION:
Elm 01 33 5915.167
END DESCRIPTION:
XS GIS Cut Line= 3
      1555329.99      6843763.03      1555443.84      6843137.82
      1555519.42      6842641.54
#Sta/Elev= 30
  4364.5 1766.74  4633.9 1767.31  4684.7 1766.22  4715.2 1768.06  4735.5 1767.71
    4753 1765.98  4816.9 1767.51  4837.2 1765.91  4898.2 1767.89  4928.7 1766.07
    4949 1761.67  4969.3 1755.99  4976.5 1752.97  4981.6 1752.91  4990.5 1750.68
    4991 1750.18  5004.2 1750.68    5020 1752.73  5038.1 1757.73  5043.1 1757.61
  5060.5 1762.08  5080.7 1764.94  5111.7 1766.41  5151.5 1765.59  5181.9 1763.11
  5202.1 1762.64  5293.2 1761.25    5371 1761.98  5444.9 1759.22    5502 1759.06
#Mann= 3 ,-1 , 0
  4364.5     .15       0  4990.5     .05       0  5004.2     .15       0
Bank Sta=4990.5,5004.2
XS Rating Curve= 0 ,0
Exp/Cntr=0.3,0.1

Type RM Length L Ch R = 1 ,5742    ,230,230,230
BEGIN DESCRIPTION:
Elm 01 33 5741.518
END DESCRIPTION:
XS GIS Cut Line= 3
      1555615.52      6843615.76      1555602.82      6843094.12
      1555556.49      6842678.29
#Sta/Elev= 30
  4478.2  1768.9    4566  1768.2    4586 1766.23    4596 1766.09    4606 1767.27
    4626 1767.73    4646 1767.05    4656 1765.68    4686 1766.33    4696 1767.29
    4746 1766.03  4846.1 1767.22  4906.1 1765.94  4926.1 1764.18  4966.1 1755.65
  4976.1 1752.71  4988.7 1750.56  4989.2 1750.06  5002.4 1750.56  5016.2 1750.93
  5046.4 1758.91  5066.5 1762.17  5086.7 1764.34  5118.8  1765.2  5187.3 1762.24
  5287.9 1760.96  5318.1 1761.75  5348.3 1761.18  5385.1 1758.89  5418.4 1759.25
#Mann= 3 ,-1 , 0
  4478.2     .15       0  4988.7     .05       0  5002.4     .15       0
Bank Sta=4988.7,5002.4
XS Rating Curve= 0 ,0
Exp/Cntr=0.3,0.1

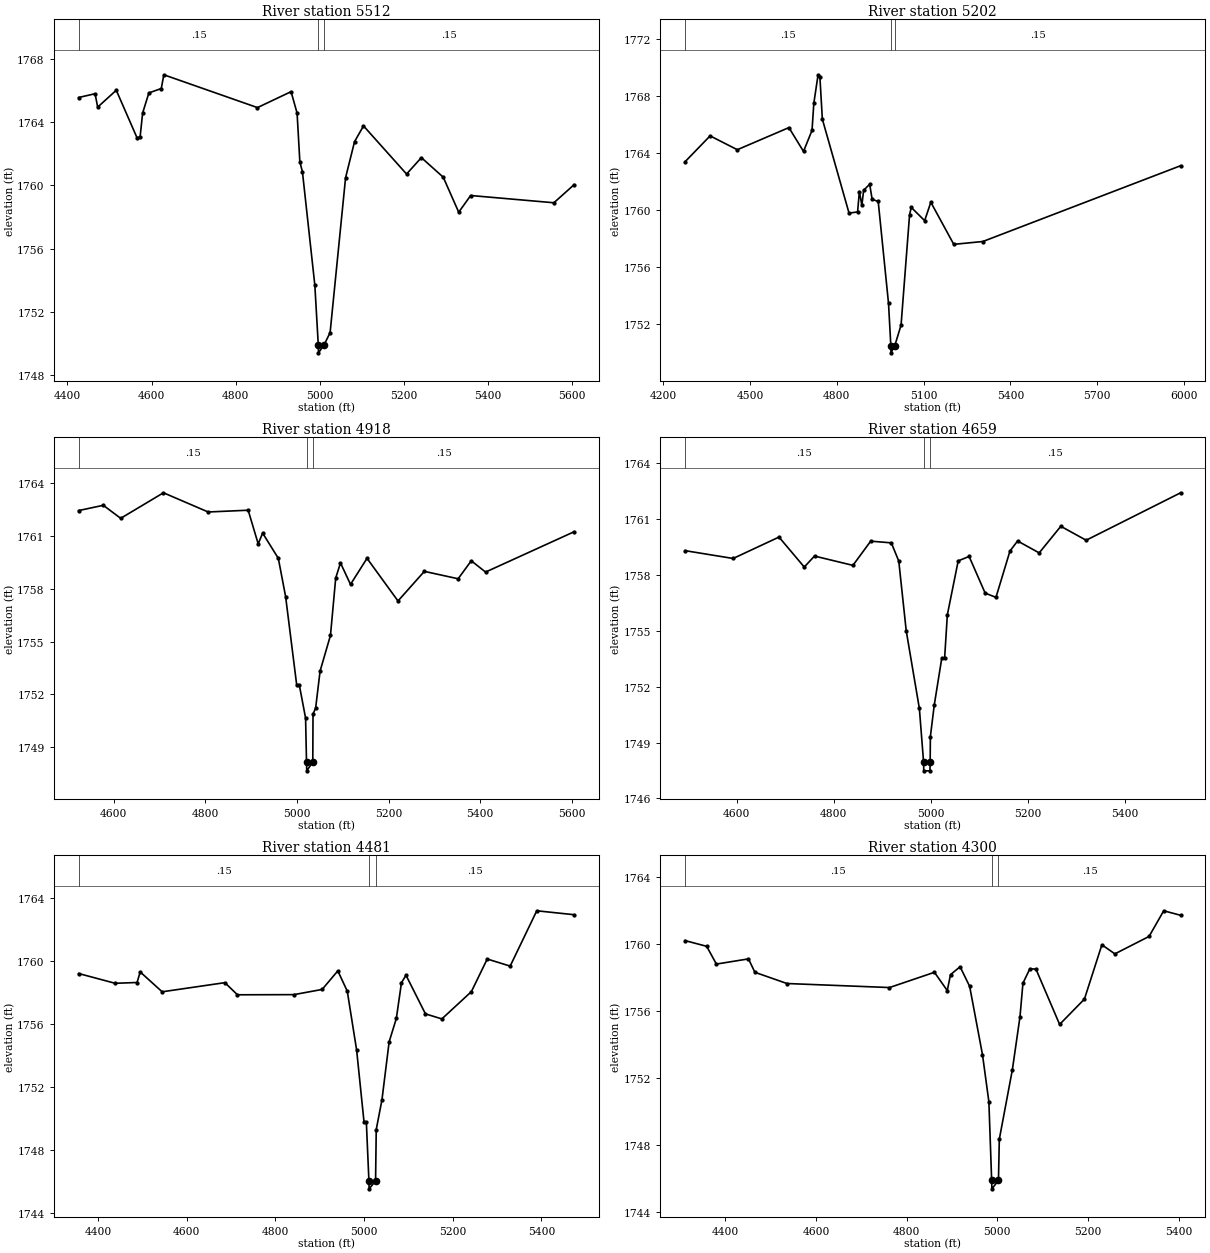
Type RM Length L Ch R = 1 ,5512    ,310,310,310
BEGIN DESCRIPTION:
Elm 01 33 5511.523
END DESCRIPTION:
XS GIS Cut Line= 3
       1556135.4      6843461.08      1555802.81       6842994.1
      1555487.24      6842478.04
#Sta/Elev= 30
  4426.7 1765.57  4465.8 1765.81    4472 1764.96  4516.2 1766.03  4565.5 1763.02
  4572.8 1763.06  4578.9 1764.59  4593.7 1765.86  4623.2 1766.14  4629.3 1767.01
  4851.9 1764.93  4931.8 1765.94  4946.1 1764.58  4952.7 1761.49  4958.8 1760.86
  4988.3 1753.68  4996.5 1749.89    4997 1749.39  5010.2 1749.89  5024.6 1750.67
  5061.4 1760.49  5082.7 1762.77    5104 1763.77  5206.4 1760.72  5241.6 1761.76
  5293.6 1760.52  5330.4  1758.3  5358.8 1759.36  5556.7  1758.9  5604.9 1760.05
#Mann= 3 ,-1 , 0
  4426.7     .15       0  4996.5     .05       0  5010.2     .15       0
Bank Sta=4996.5,5010.2
XS Rating Curve= 0 ,0
Exp/Cntr=0.3,0.1

Type RM Length L Ch R = 1 ,5202    ,284,284,284
BEGIN DESCRIPTION:
Elm 01 33 5202.203
END DESCRIPTION:
XS GIS Cut Line= 3
      1556475.66      6843428.65      1556056.87      6842836.83
      1555541.57      6841992.45
#Sta/Elev= 30
    4275 1763.39  4361.5  1765.2  4455.7 1764.23  4634.1 1765.78  4684.6 1764.11
  4714.1 1765.59  4720.3 1767.48    4735 1769.48  4741.3 1769.33  4749.8 1766.37
  4842.1 1759.79  4871.7 1759.87  4877.8  1761.3  4886.5 1760.33  4892.6 1761.39
  4913.5 1761.81  4922.1 1760.75    4943 1760.61  4978.7 1753.46  4986.7  1750.5
  4987.2    1750  5000.4  1750.5  5022.1 1751.95  5051.5 1759.67  5057.3 1760.19
  5103.7 1759.26    5125 1760.55  5204.4  1757.6  5305.1  1757.8  5989.2 1763.11
#Mann= 3 ,-1 , 0
    4275     .15       0  4986.7     .05       0  5000.4     .15       0
Bank Sta=4986.7,5000.4
XS Rating Curve= 0 ,0
Exp/Cntr=0.3,0.1

Type RM Length L Ch R = 1 ,4918    ,259,259,259
BEGIN DESCRIPTION:
Elm 01 33 4917.911
END DESCRIPTION:
XS GIS Cut Line= 3
      1556535.66       6843150.5      1556307.66      6842732.54
      1556019.14      6842200.66
#Sta/Elev= 30
  4523.9 1762.43  4577.7 1762.73  4615.7 1761.99    4709 1763.44  4806.5 1762.35
  4893.8 1762.45  4915.7 1760.54  4925.4 1761.15  4959.6 1759.72  4975.5 1757.55
  4999.7 1752.53  5005.4 1752.53  5019.1 1750.65  5021.1 1748.16  5021.6 1747.66
  5034.8 1748.16  5035.3 1750.88    5041 1751.22  5050.7 1753.32  5073.4 1755.35
  5084.8  1758.6  5095.2 1759.46  5117.1 1758.24  5153.1 1759.72  5220.7  1757.3
  5278.2 1758.98  5351.9 1758.56  5380.6 1759.58  5411.8 1758.94  5605.1 1761.23
#Mann= 3 ,-1 , 0
  4523.9     .15       0  5021.1     .05       0  5034.8     .15       0
Bank Sta=5021.1,5034.8
XS Rating Curve= 0 ,0
Exp/Cntr=0.3,0.1

Type RM Length L Ch R = 1 ,4659    ,178,178,178
BEGIN DESCRIPTION:
Elm 01 33 4659.435
END DESCRIPTION:
XS GIS Cut Line= 3
      1556761.34      6843018.53        1556480.        6842563.
      1556264.84      6842126.22
#Sta/Elev= 30
  4493.4 1759.31  4592.5 1758.89  4687.1 1760.04  4739.2 1758.43  4760.4 1759.02
  4839.6 1758.52  4876.3 1759.82  4918.8 1759.73  4934.2 1758.75  4949.6    1755
  4976.7 1750.83  4985.3 1747.98  4985.8 1747.48  4998.5 1747.48    4999 1747.98
  4999.4 1749.32  5007.5 1751.03  5022.9 1753.53  5028.8 1753.53  5034.4 1755.86
  5056.8 1758.76  5079.3    1759  5112.4 1757.03  5134.7  1756.8  5163.6 1759.29
  5179.3 1759.83  5223.9 1759.19  5268.5 1760.62  5320.8 1759.87  5515.7 1762.42
#Mann= 3 ,-1 , 0
  4493.4     .15       0  4985.3     .05       0    4999     .15       0
Bank Sta=4985.3,4999
XS Rating Curve= 0 ,0
Exp/Cntr=0.3,0.1

Type RM Length L Ch R = 1 ,4481    ,181,181,181
BEGIN DESCRIPTION:
Elm 01 33 4481.474
END DESCRIPTION:
XS GIS Cut Line= 3
      1557108.56      6842990.76      1556657.29      6842532.16
      1556431.48      6842115.74
#Sta/Elev= 30
  4356.6 1759.19  4438.9 1758.57  4488.3 1758.62  4495.4 1759.29  4544.9 1758.03
  4686.3 1758.61  4714.6 1757.84  4841.9 1757.85  4905.6 1758.18  4940.9 1759.36
  4962.2 1758.07  4983.3 1754.33    5000 1749.76  5005.2 1749.76    5011 1746.03
  5011.5 1745.53    5026 1746.03  5027.5 1749.29  5040.4 1751.18  5056.6 1754.86
  5072.8 1756.34  5084.4 1758.61  5094.6 1759.08  5138.4 1756.63  5175.4 1756.31
    5242 1758.04  5277.7 1760.11  5329.4 1759.66  5389.4 1763.17  5473.7 1762.92
#Mann= 3 ,-1 , 0
  4356.6     .15       0    5011     .05       0    5026     .15       0
Bank Sta=5011,5026
XS Rating Curve= 0 ,0
Exp/Cntr=0.3,0.1

Type RM Length L Ch R = 1 ,4300    ,234,234,234
BEGIN DESCRIPTION:
Elm 01 33 4299.921
END DESCRIPTION:
XS GIS Cut Line= 3
      1557278.74      6842931.77      1556803.26      6842433.81
      1556639.91      6842063.87
#Sta/Elev= 30
  4311.5 1760.18  4359.1 1759.84  4380.5 1758.78  4451.3 1759.09  4465.4 1758.29
  4536.2 1757.62  4762.3 1757.38  4861.4 1758.29  4889.7  1757.2  4896.9 1758.15
    4918 1758.62  4939.1 1757.45  4967.4 1753.37  4981.5 1750.56  4987.6 1745.87
  4988.1 1745.37  5002.6 1745.87  5004.5 1748.33  5033.3 1752.48  5050.1 1755.64
  5056.6 1757.64  5071.9  1758.5  5085.3 1758.48  5137.5 1755.18  5192.2 1756.69
  5230.7 1759.93  5259.4 1759.39  5334.8 1760.43  5367.1 1761.96  5404.4 1761.69
#Mann= 3 ,-1 , 0
  4311.5     .15       0  4987.6     .05       0  5002.6     .15       0
Bank Sta=4987.6,5002.6
XS Rating Curve= 0 ,0
Exp/Cntr=0.3,0.1

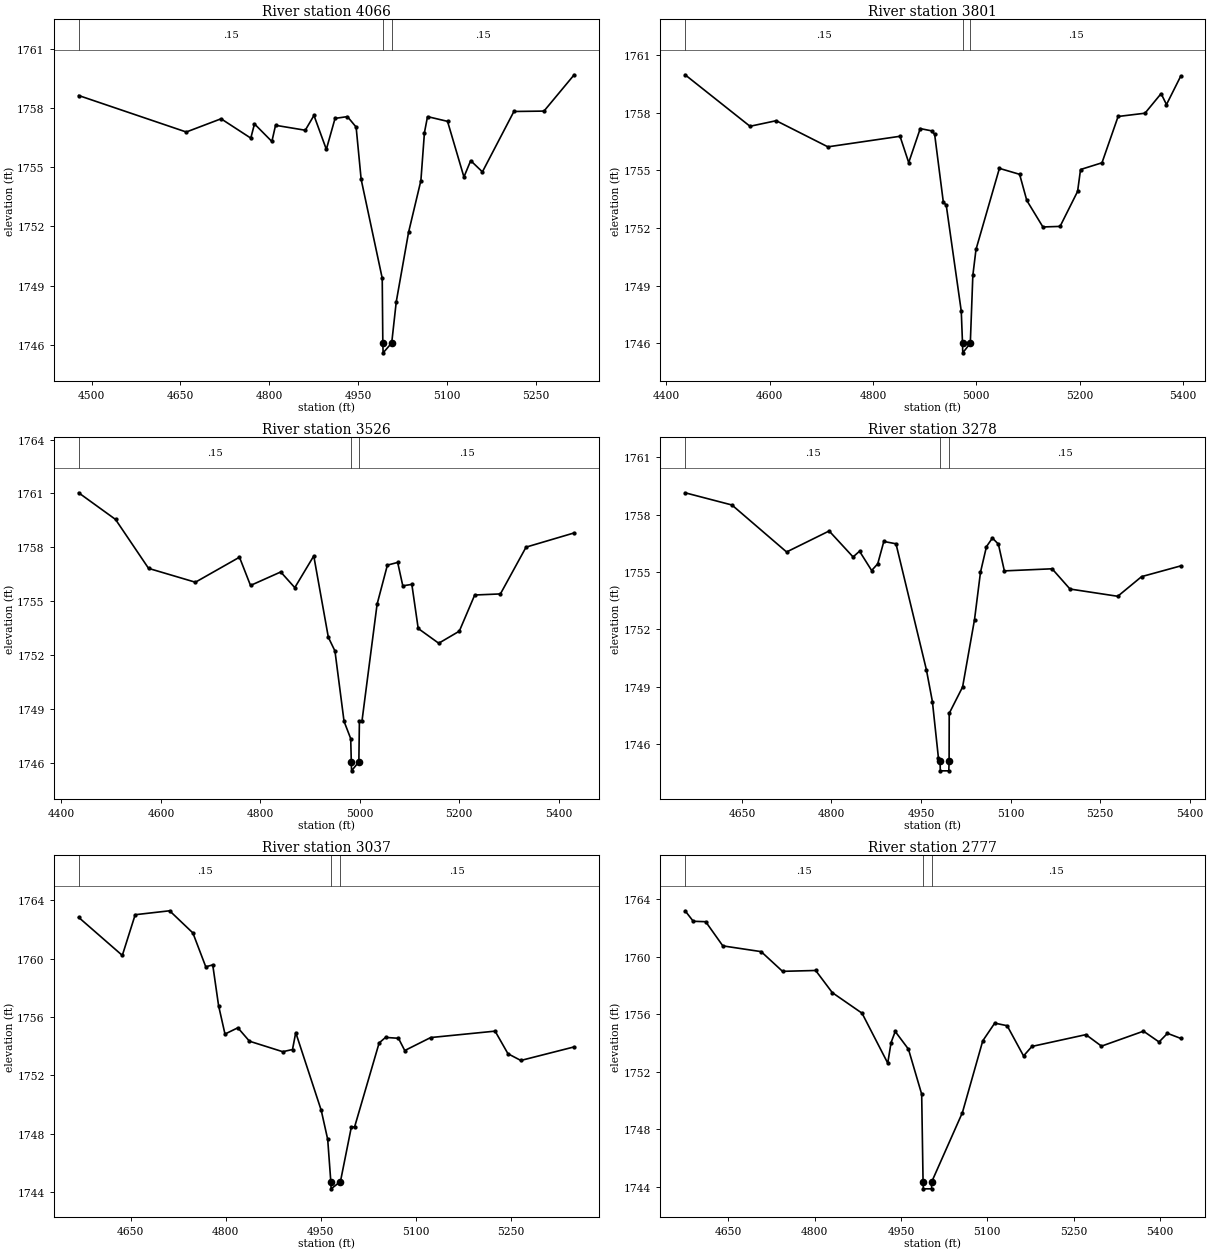
Type RM Length L Ch R = 1 ,4066    ,265,265,265
BEGIN DESCRIPTION:
Elm 01 33 4065.689
END DESCRIPTION:
XS GIS Cut Line= 3
      1557313.43      6842754.65       1557007.2      6842331.92
      1556921.06      6842028.92
#Sta/Elev= 30
    4478 1758.63  4659.8 1756.78  4718.6 1757.45  4768.8 1756.47    4775 1757.19
  4804.4  1756.3  4810.6 1757.12  4860.8 1756.87  4875.5 1757.62  4896.4  1755.9
  4911.1 1757.47    4932 1757.56  4946.7 1757.03  4955.2 1754.38  4990.8 1749.37
  4991.8 1746.09  4992.3 1745.59  5006.8 1746.09  5014.5 1748.18  5035.3  1751.7
  5056.1 1754.32  5062.1 1756.75  5067.3 1757.56  5101.1 1757.32  5128.8  1754.5
  5140.2 1755.33    5160 1754.76  5213.2 1757.82    5264 1757.84    5315 1759.68
#Mann= 3 ,-1 , 0
    4478     .15       0  4991.8     .05       0  5006.8     .15       0
Bank Sta=4991.8,5006.8
XS Rating Curve= 0 ,0
Exp/Cntr=0.3,0.1

Type RM Length L Ch R = 1 ,3801    ,275,275,275
BEGIN DESCRIPTION:
Elm 01 33 3800.556
END DESCRIPTION:
XS GIS Cut Line= 3
      1557466.19      6842695.59      1557213.33      6842192.01
      1557105.49       6841811.6
#Sta/Elev= 30
  4436.5 1759.98  4562.1  1757.3  4612.8 1757.59  4712.8 1756.23  4852.4 1756.78
  4869.2 1755.41  4891.5 1757.18  4913.8 1757.06  4919.4 1756.88  4936.2 1753.35
  4941.8  1753.2  4970.9 1747.68  4973.3 1746.01  4973.8 1745.51  4988.4 1746.01
  4993.3 1749.54  4999.4 1750.89  5044.7 1755.11  5083.8  1754.8  5097.7 1753.44
  5128.9 1752.06  5162.1 1752.09    5196 1753.91  5201.7 1755.05  5243.2  1755.4
  5274.4 1757.81  5326.4 1757.98  5357.6    1759    5368 1758.43  5395.4  1759.9
#Mann= 3 ,-1 , 0
  4436.5     .15       0  4973.3     .05       0  4988.4     .15       0
Bank Sta=4973.3,4988.4
XS Rating Curve= 0 ,0
Exp/Cntr=0.3,0.1

Type RM Length L Ch R = 1 ,3526    ,248,248,248
BEGIN DESCRIPTION:
Elm 01 33 3525.622
END DESCRIPTION:
XS GIS Cut Line= 3
      1557716.23      6842584.56      1557457.18      6842081.88
      1557348.16      6841664.38
#Sta/Elev= 30
  4434.5 1761.04  4508.7 1759.56  4575.2 1756.84  4669.4 1756.07  4758.1 1757.46
  4780.3 1755.89  4841.1 1756.64  4869.4 1755.77  4907.6 1757.53  4936.9 1753.01
  4950.2 1752.25  4968.5 1748.34  4981.9 1747.38  4983.1 1746.09  4983.6 1745.59
  4998.3 1746.09  4999.4 1748.36  5004.6 1748.36    5035 1754.85  5055.7 1757.02
  5076.4 1757.17  5086.7 1755.87  5104.9 1755.95  5117.7  1753.5    5159 1752.68
  5200.4 1753.35  5231.4 1755.36  5283.1 1755.42  5334.7 1758.02  5431.5 1758.81
#Mann= 3 ,-1 , 0
  4434.5     .15       0  4983.1     .05       0  4998.3     .15       0
Bank Sta=4983.1,4998.3
XS Rating Curve= 0 ,0
Exp/Cntr=0.3,0.1

Type RM Length L Ch R = 1 ,3278    ,241,241,241
BEGIN DESCRIPTION:
Elm 01 33 3278.112
END DESCRIPTION:
XS GIS Cut Line= 3
       1557773.5      6842475.11      1557690.17      6842037.68
      1557683.23      6841652.64
#Sta/Elev= 30
  4554.7 1759.15  4633.2 1758.51  4724.8 1756.05  4796.1 1757.15  4836.2 1755.79
    4847 1756.09  4867.3 1755.08  4877.5 1755.43  4887.7  1756.6  4908.1 1756.48
    4959 1749.89  4969.1 1748.22  4979.3 1745.24  4981.9 1745.09  4982.4 1744.59
  4996.6 1744.59  4997.1 1745.09  4997.3  1747.6  5019.7 1748.98  5039.7 1752.51
  5049.7 1754.99  5059.7 1756.33  5069.7 1756.78  5079.7 1756.46  5089.7 1755.06
  5169.7 1755.17  5199.7 1754.11  5279.7 1753.73  5319.7 1754.76  5385.1 1755.32
#Mann= 3 ,-1 , 0
  4554.7     .15       0  4981.9     .05       0  4997.1     .15       0
Bank Sta=4981.9,4997.1
XS Rating Curve= 0 ,0
Exp/Cntr=0.3,0.1

Type RM Length L Ch R = 1 ,3037    ,260,260,260
BEGIN DESCRIPTION:
Elm 01 33 3037.179
END DESCRIPTION:
XS GIS Cut Line= 3
      1557981.83       6842416.1      1557915.51      6841989.22
      1557853.37      6841645.29
#Sta/Elev= 30
    4568 1762.84  4636.9 1760.23  4657.2 1763.02  4711.5 1763.29  4748.2 1761.77
  4768.5 1759.45  4779.5 1759.58  4788.7 1756.79  4798.8 1754.84  4819.1 1755.27
  4837.4 1754.35  4889.9 1753.63  4905.3 1753.78  4910.4 1754.94  4950.6 1749.61
  4960.8 1747.62  4965.7 1744.73  4966.2 1744.23  4980.9 1744.73  4998.1 1748.47
  5003.2 1748.47  5041.9 1754.23    5052 1754.61  5072.4 1754.55  5082.3 1753.71
  5123.2  1754.6  5224.8 1755.04  5245.1 1753.49  5265.4 1753.03  5349.5 1753.96
#Mann= 3 ,-1 , 0
    4568     .15       0  4965.7     .05       0  4980.9     .15       0
Bank Sta=4965.7,4980.9
XS Rating Curve= 0 ,0
Exp/Cntr=0.3,0.1

Type RM Length L Ch R = 1 ,2777    ,234,234,234
BEGIN DESCRIPTION:
Elm 01 33 2777.037
END DESCRIPTION:
XS GIS Cut Line= 3
      1558367.23      6842304.97      1558155.85       6841935.8
      1557895.05      6841586.28
#Sta/Elev= 30
  4574.6  1763.2  4588.8 1762.47  4610.4 1762.44  4640.2 1760.76  4706.8 1760.36
    4744 1758.99  4801.6 1759.05  4830.5 1757.51  4882.2 1756.08  4926.9 1752.61
  4932.7 1754.04  4939.9 1754.81  4962.9 1753.58  4985.9 1750.45  4988.3 1744.37
  4988.8 1743.87    5003 1743.87  5003.5 1744.37  5056.7 1749.17  5092.1 1754.16
  5112.9 1755.39  5134.5 1755.21    5163 1753.11  5177.6 1753.77  5271.4 1754.59
  5298.5 1753.79  5371.5 1754.83  5398.6 1754.08  5413.2 1754.68  5436.1 1754.33
#Mann= 3 ,-1 , 0
  4574.6     .15       0  4988.3     .05       0  5003.5     .15       0
Bank Sta=4988.3,5003.5
XS Rating Curve= 0 ,0
Exp/Cntr=0.3,0.1

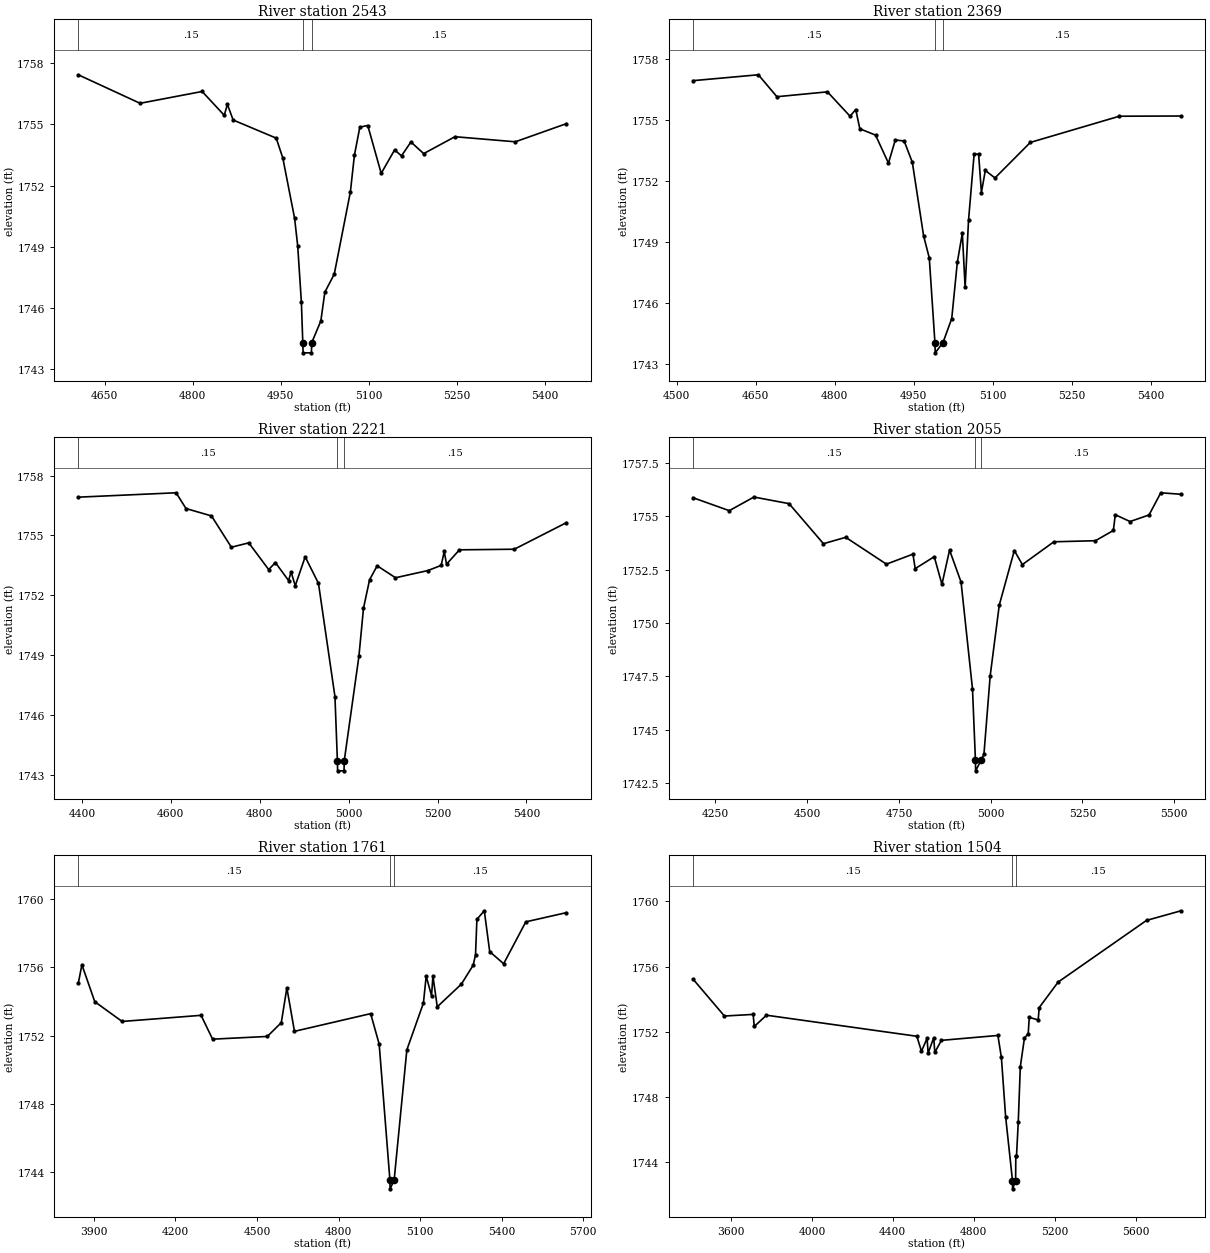
Type RM Length L Ch R = 1 ,2543    ,174,174,174
BEGIN DESCRIPTION:
Elm 01 33 2543.213
END DESCRIPTION:
XS GIS Cut Line= 3
      1558634.62      6841864.03      1558261.12      6841735.82
      1557878.88      6841524.42
#Sta/Elev= 30
  4605.1 1757.44  4710.4 1756.04  4816.2 1756.62  4853.9 1755.45  4859.2 1755.99
    4869 1755.22  4942.4 1754.33  4953.6 1753.36  4973.7  1750.4    4979 1749.05
  4985.3 1746.28  4987.7 1744.29  4988.2 1743.79  5002.4 1743.79  5002.9 1744.29
  5018.4 1745.35  5025.3 1746.77  5041.3 1747.65  5068.8 1751.69  5075.6 1753.48
  5084.9 1754.87  5098.4 1754.95  5121.3  1752.6  5144.1 1753.75  5155.9 1753.46
  5171.9 1754.14  5193.7 1753.57    5247  1754.4  5349.8 1754.15  5436.8 1755.04
#Mann= 3 ,-1 , 0
  4605.1     .15       0  4987.7     .05       0  5002.9     .15       0
Bank Sta=4987.7,5002.9
XS Rating Curve= 0 ,0
Exp/Cntr=0.3,0.1

Type RM Length L Ch R = 1 ,2369    ,148,148,148
BEGIN DESCRIPTION:
Elm 01 33 2368.977
END DESCRIPTION:
XS GIS Cut Line= 3
      1558752.68      6841749.45      1558315.89      6841578.37
      1557884.64      6841426.54
#Sta/Elev= 30
  4530.9 1756.94  4655.1 1757.23  4690.3 1756.15  4786.2 1756.39  4829.1 1755.19
  4839.9 1755.52  4847.7 1754.57  4877.5 1754.26    4902 1752.88    4915 1754.02
  4931.8 1753.97  4947.3 1752.92  4968.7  1749.3  4979.5 1748.21  4990.2 1744.04
  4990.7 1743.54  5005.4 1744.04  5022.1 1745.23  5032.7    1748  5042.2 1749.43
  5047.5 1746.76    5054 1750.08  5064.6 1753.33  5073.1 1753.32  5078.4 1751.43
  5085.8 1752.52  5104.1 1752.15  5171.3  1753.9  5340.2 1755.19  5457.2  1755.2
#Mann= 3 ,-1 , 0
  4530.9     .15       0  4990.2     .05       0  5005.4     .15       0
Bank Sta=4990.2,5005.4
XS Rating Curve= 0 ,0
Exp/Cntr=0.3,0.1

Type RM Length L Ch R = 1 ,2221    ,166,166,166
BEGIN DESCRIPTION:
Elm 01 33 2220.83
END DESCRIPTION:
XS GIS Cut Line= 3
      1558901.98      6841714.73      1558357.47      6841443.57
      1557881.18      6841329.32
#Sta/Elev= 30
  4391.7 1756.92  4611.8 1757.14  4634.1 1756.35  4691.4 1755.98  4736.2 1754.41
  4775.3 1754.63  4820.1 1753.29  4835.2 1753.64  4864.9 1752.74  4870.5 1753.17
  4879.9 1752.48  4902.2 1753.93  4932.1  1752.6  4969.2 1746.92  4974.7  1743.7
  4975.2  1743.2  4989.6  1743.2  4990.1  1743.7  5023.1 1748.94  5033.4 1751.35
  5047.1 1752.78  5064.2 1753.48  5105.4 1752.88  5178.2 1753.24  5208.2  1753.5
  5215.1  1754.2  5220.2 1753.56  5249.3 1754.28  5372.7 1754.31  5489.8 1755.64
#Mann= 3 ,-1 , 0
  4391.7     .15       0  4974.7     .05       0  4990.1     .15       0
Bank Sta=4974.7,4990.1
XS Rating Curve= 0 ,0
Exp/Cntr=0.3,0.1

Type RM Length L Ch R = 1 ,2055    ,294,294,294
BEGIN DESCRIPTION:
Elm 01 33 2055.306
END DESCRIPTION:
XS GIS Cut Line= 3
      1559186.66      6841520.27      1558407.47      6841293.57
      1557912.43      6841138.35
#Sta/Elev= 30
  4188.5 1755.88  4287.6 1755.27  4354.7 1755.91  4450.6  1755.6  4544.3 1753.72
  4604.9 1754.02  4715.9 1752.76  4788.2 1753.23  4794.3 1752.55  4846.3 1753.11
  4867.2 1751.81    4888 1753.42  4919.3 1751.92  4950.5  1746.9  4958.5 1743.56
    4959 1743.06  4973.9 1743.56  4981.7 1743.84  4998.7 1747.52  5023.5 1750.84
  5064.5  1753.4  5086.4 1752.74  5172.3 1753.81  5285.5 1753.86  5334.4 1754.34
  5339.7 1755.08  5379.9 1754.76  5431.7 1755.07  5463.7 1756.11  5518.8 1756.04
#Mann= 3 ,-1 , 0
  4188.5     .15       0  4958.5     .05       0  4973.9     .15       0
Bank Sta=4958.5,4973.9
XS Rating Curve= 0 ,0
Exp/Cntr=0.3,0.1

Type RM Length L Ch R = 1 ,1761    ,257,257,257
BEGIN DESCRIPTION:
Elm 01 33 1761.238
END DESCRIPTION:
XS GIS Cut Line= 3
        1559632.      6841296.32      1558507.01       6841030.7
      1557878.39      6840911.21
#Sta/Elev= 30
  3842.5 1755.06  3855.9 1756.16  3903.3 1753.99  4003.8 1752.83  4294.4 1753.19
  4336.7 1751.79  4538.1 1751.95  4589.5 1752.76    4610  1754.8    4638 1752.25
  4918.3 1753.29  4949.6  1751.5  4989.2  1743.5  4989.7    1743  5004.6  1743.5
  5051.4 1751.16  5112.4 1753.91  5122.6 1755.49  5142.3 1754.34  5147.4  1755.5
  5163.3 1753.69  5251.9 1755.02  5295.7 1756.14  5304.1 1756.75  5309.2 1758.83
  5336.4 1759.33  5356.3 1756.93  5407.6 1756.22  5489.1 1758.68  5638.3 1759.22
#Mann= 3 ,-1 , 0
  3842.5     .15       0  4989.2     .05       0  5004.6     .15       0
Bank Sta=4989.2,5004.6
XS Rating Curve= 0 ,0
Exp/Cntr=0.3,0.1

Type RM Length L Ch R = 1 ,1504    ,327,327,327
BEGIN DESCRIPTION:
Elm 01 33 1504.455
END DESCRIPTION:
XS GIS Cut Line= 3
      1560074.73      6841249.45      1558543.47      6840785.91
      1557748.34      6840614.41
#Sta/Elev= 30
  3411.7 1755.24  3567.5 1752.97  3709.6 1753.07  3714.9 1752.33  3775.5 1753.02
  4518.9 1751.73  4541.7 1750.81  4569.4  1751.6  4574.7  1750.7  4602.4 1751.64
  4607.6 1750.74  4640.5 1751.48  4919.6 1751.78  4936.9 1750.43  4957.8  1746.8
  4991.8 1742.88  4992.3 1742.38  5007.2 1742.88  5008.2 1744.39  5011.6 1744.39
  5020.3 1746.46  5030.5 1749.87  5050.9 1751.62  5069.5 1751.89  5074.7 1752.89
  5118.8 1752.73    5124 1753.49  5217.4 1755.05  5654.5 1758.83    5825 1759.42
#Mann= 3 ,-1 , 0
  3411.7     .15       0  4991.8     .05       0  5007.2     .15       0
Bank Sta=4991.8,5007.2
XS Rating Curve= 0 ,0
Exp/Cntr=0.3,0.1

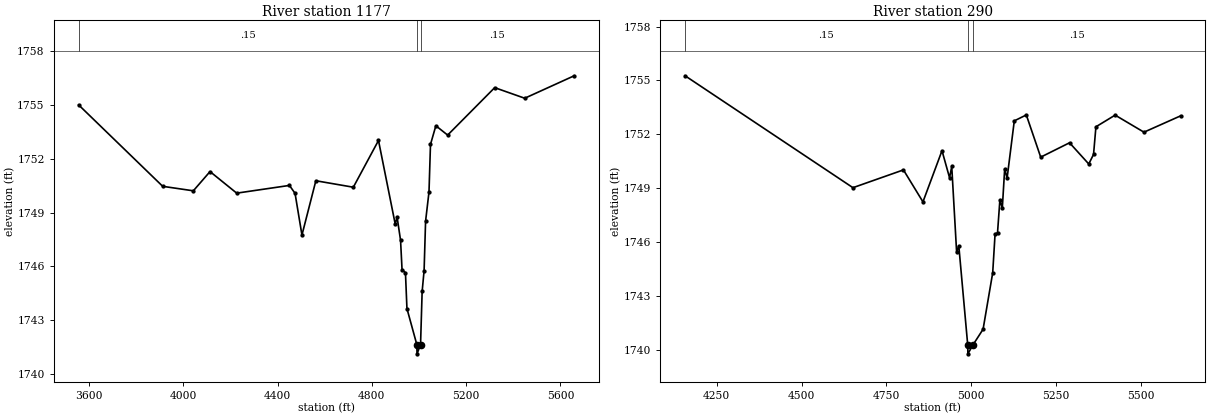
Type RM Length L Ch R = 1 ,1177    ,887,887,887
BEGIN DESCRIPTION:
Elm 01 33 1176.927
END DESCRIPTION:
XS GIS Cut Line= 3
       1560064.3      6841197.36      1559038.26      6840770.28
       1558247.7      6840172.16
#Sta/Elev= 30
  3555.8 1754.99  3912.5 1750.46  4042.5 1750.21  4113.3 1751.28  4226.6 1750.08
  4450.3 1750.51  4474.1 1750.07  4503.4 1747.75  4562.4 1750.77  4721.4 1750.41
  4828.2 1753.01    4899 1748.37  4907.3 1748.73  4921.8 1747.46  4928.1 1745.83
  4942.6 1745.65  4948.9 1743.66  4991.1 1741.64  4991.6 1741.14  5006.6 1741.64
  5013.4 1744.61  5021.7 1745.77    5028 1748.52  5042.5 1750.15  5048.8 1752.79
  5071.6 1753.83  5121.6 1753.31  5321.3 1755.95  5448.7 1755.36  5658.5 1756.61
#Mann= 3 ,-1 , 0
  3555.8     .15       0  4991.1     .05       0  5006.6     .15       0
Bank Sta=4991.1,5006.6
XS Rating Curve= 0 ,0
Exp/Cntr=0.3,0.1

Type RM Length L Ch R = 1 ,290     ,0,0,0
BEGIN DESCRIPTION:
Elm 01 33 290.107
END DESCRIPTION:
XS GIS Cut Line= 3
      1560163.24      6841244.21      1559633.45      6840588.36
      1559194.53      6840155.72
#Sta/Elev= 30
  4156.9 1755.26  4651.2 1749.03  4799.9 1750.02  4857.4 1748.24  4913.5 1751.09
  4935.8 1749.58  4942.2 1750.21  4956.6 1745.43    4963 1745.79  4989.2 1740.28
  4989.7 1739.78  5004.8 1740.28  5034.5 1741.15  5062.8 1744.29  5069.8 1746.45
    5077 1746.52    5084 1748.35  5091.1 1747.89  5098.1 1750.08  5105.2 1749.56
  5126.4 1752.75  5161.8 1753.08  5204.2 1750.73  5289.1 1751.53  5345.7 1750.35
  5359.8 1750.88  5366.8 1752.42  5423.4 1753.07  5508.3 1752.12  5616.3 1753.03
#Mann= 3 ,-1 , 0
  4156.9     .15       0  4989.2     .05       0  5004.8     .15       0
Bank Sta=4989.2,5004.8
XS Rating Curve= 0 ,0
Exp/Cntr=0.3,0.1

Chan Stop Cuts=-1
Use User Specified Reach Order=0
Composite Channel Slope=5