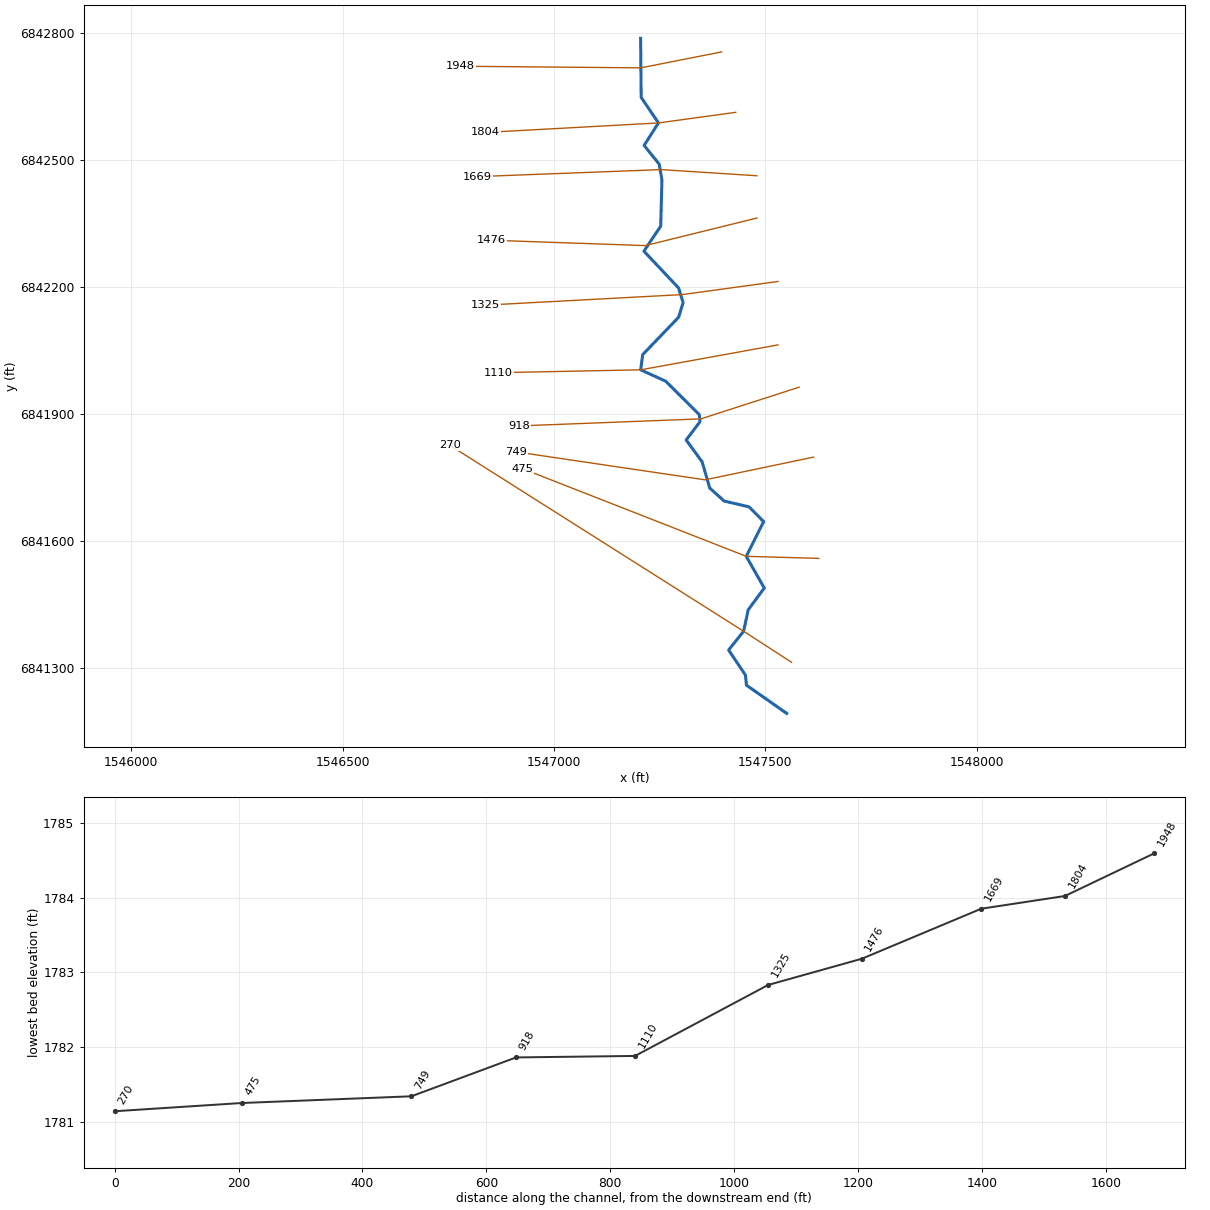
--- Elm 01 34.prj (project) ---

Proj Title=Elm 01 34 Base Level Engineering
Current Plan=p01
Default Exp/Contr=0.3,0.1
English Units
Geom File=g01
Flow File=f01
Plan File=p01
BEGIN DESCRIPTION:
Elm 01 34
END DESCRIPTION:

--- Elm 01 34.p01 (plan) ---

Plan Title=Multiple Run
Short Identifier=Multiple
Geom File=g01
Flow File=f01
Subcritical Flow
K Sum by GR= 0
Std Step Tol= 0.01
Critical Tol= 0.01
Num of Std Step Trials= 20
Max Error Tol= 0.3
Flow Tol Ratio= 0.001
Split Flow NTrial= 30
Split Flow Tol= 0.02
Split Flow Ratio= 0.02
Log Output Level= 0
Friction Slope Method= 1
Unsteady Friction Slope Method= 2
Unsteady Bridges Friction Slope Method= 1
Parabolic Critical Depth
Global Vel Dist=  1 , 1 , 1
Global Log Level= 0
CheckData=True
Encroach Param= -1, 0, 0, 0
BEGIN DESCRIPTION:
Multiple Run
END DESCRIPTION:

--- Elm 01 34.f01 (steady flow) ---

Flow Title=Multiple
Number of Profiles=7
Profile Names=10-year,25-year,50-year,1pct_min,100-year,1pct_plu,500-year
River Rch & RM= Elm 01 34,Reach-1,1948
     115     152     181     134     214     295     305
Boundary for River Rch & Prof#=Elm 01 34,Reach-1,1
Up Type=0
Dn Type=3
Dn Slope=0.005
Boundary for River Rch & Prof#=Elm 01 34,Reach-1,2
Up Type=0
Dn Type=3
Dn Slope=0.005
Boundary for River Rch & Prof#=Elm 01 34,Reach-1,3
Up Type=0
Dn Type=3
Dn Slope=0.005
Boundary for River Rch & Prof#=Elm 01 34,Reach-1,4
Up Type=0
Dn Type=3
Dn Slope=0.005
Boundary for River Rch & Prof#=Elm 01 34,Reach-1,5
Up Type=0
Dn Type=3
Dn Slope=0.005
Boundary for River Rch & Prof#=Elm 01 34,Reach-1,6
Up Type=0
Dn Type=3
Dn Slope=0.005
Boundary for River Rch & Prof#=Elm 01 34,Reach-1,7
Up Type=0
Dn Type=3
Dn Slope=0.005

--- Elm 01 34.g01 (geometry) ---

Geom Title=Existing Conditions

River Reach=Elm 01 34,Reach-1
Reach XY= 30
      1547205.00      6842788.00      1547206.33      6842648.41
      1547247.21      6842587.90      1547213.28      6842534.78
      1547249.00      6842490.45      1547255.41      6842453.19
      1547252.54      6842343.86      1547212.81      6842284.59
      1547294.78      6842197.68      1547305.58      6842163.00
      1547294.80      6842128.33      1547209.94      6842039.95
      1547205.17      6842004.04      1547264.38      6841977.11
      1547343.77      6841898.02      1547345.40      6841881.35
      1547312.77      6841838.09      1547350.55      6841786.32
      1547368.47      6841724.44      1547402.51      6841693.75
      1547461.67      6841679.84      1547495.97      6841645.01
      1547454.78      6841563.00      1547497.44      6841488.00
      1547459.39      6841436.35      1547448.64      6841385.72
      1547413.07      6841341.31      1547453.02      6841281.95
      1547455.32      6841258.16      1547550.45      6841191.53

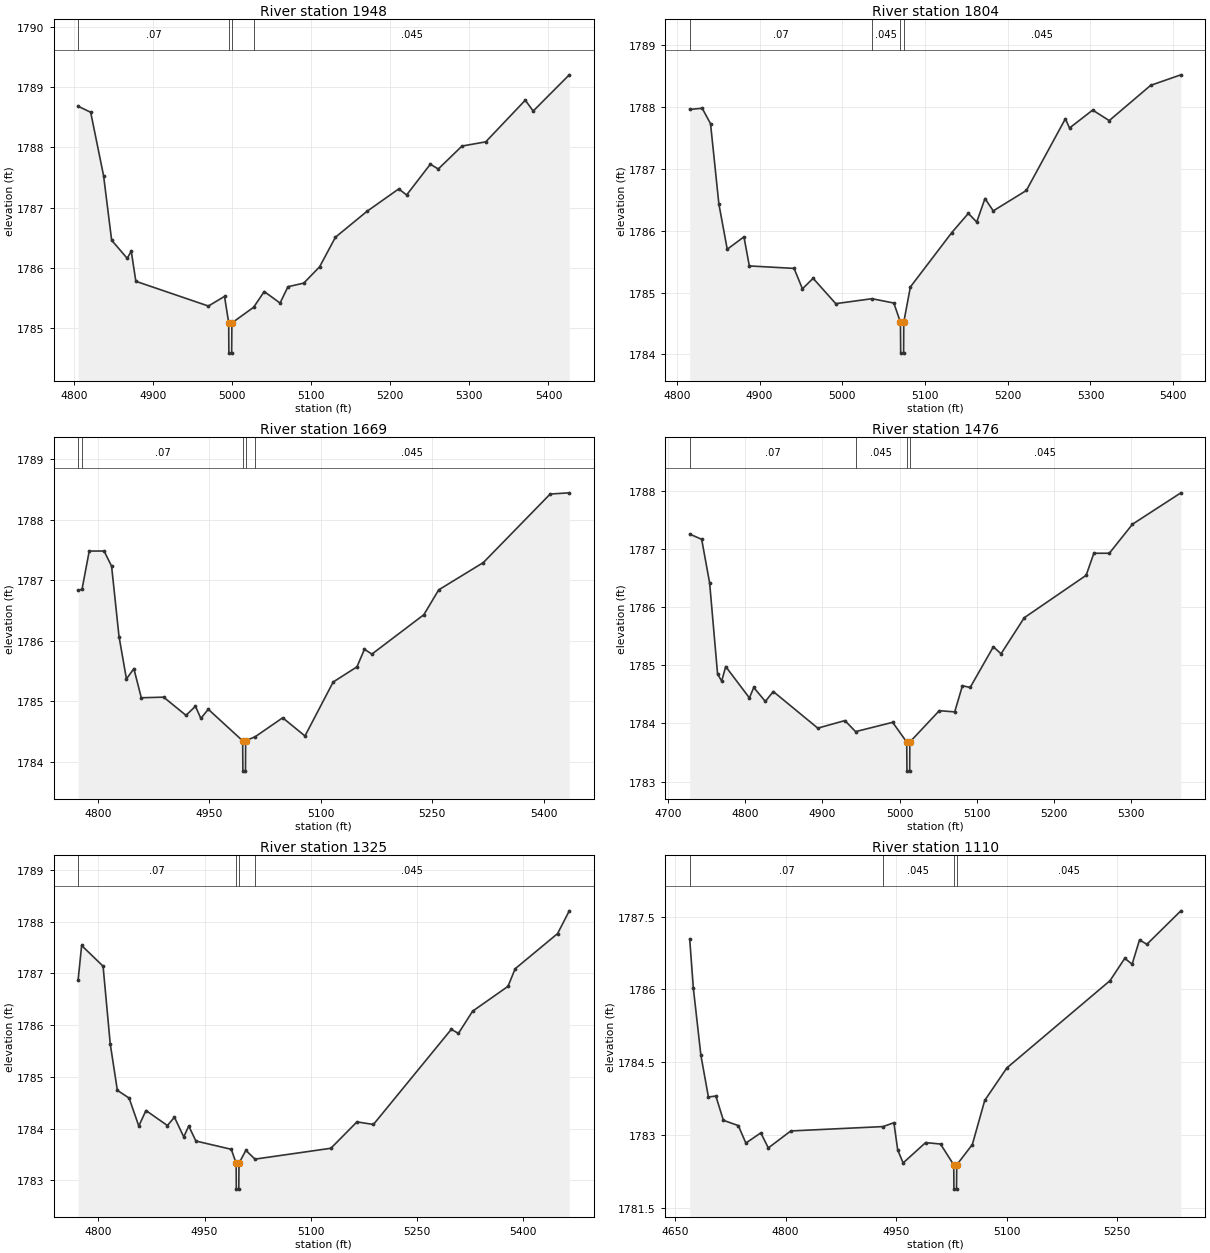
Type RM Length L Ch R = 1,1948,144,144,144
BEGIN DESCRIPTION:
Elm 01 34 1947.849
END DESCRIPTION:
XS GIS Cut Line= 3
      1547396.58      6842755.89      1547205.67      6842718.20
      1546779.38      6842722.00
#Sta/Elev= 30
  4805.4 1788.68  4821.3 1788.58  4837.6 1787.53  4847.8 1786.46  4867.5 1786.16
  4872.6 1786.28  4878.4 1785.78  4970.1 1785.37  4990.5 1785.53  4995.8 1785.09
  4996.0 1784.59  4999.5 1784.59  4999.8 1785.09  5027.3 1785.35  5040.7 1785.61
  5060.7 1785.42  5070.7 1785.69  5090.7 1785.75  5110.7 1786.02  5130.7 1786.51
  5170.7 1786.94  5210.7 1787.31  5220.7 1787.21  5250.7 1787.72  5260.7 1787.64
  5290.7 1788.02  5320.7 1788.09  5370.7 1788.78  5380.7 1788.60  5426.3 1789.20
#Mann=4,-1,0
  4805.4    0.07       0  4995.8    0.07       0  4999.8    0.07       0
  5027.3   0.045       0
Bank Sta=4995.8,4999.8
Exp/Cntr=0.3,0.1

Type RM Length L Ch R = 1,1804,135,135,135
BEGIN DESCRIPTION:
Elm 01 34 1804.144
END DESCRIPTION:
XS GIS Cut Line= 3
      1547430.00      6842613.00      1547247.21      6842587.90
      1546838.53      6842565.47
#Sta/Elev= 30
  4815.5 1787.96  4830.6 1787.98  4840.7 1787.73  4850.8 1786.43  4860.9 1785.70
  4881.1 1785.90  4887.6 1785.43  4941.7 1785.39  4951.8 1785.06  4964.7 1785.23
  4992.1 1784.82  5035.9 1784.90  5062.3 1784.83  5070.3 1784.52  5070.6 1784.02
  5074.1 1784.02  5074.3 1784.52  5082.3 1785.09  5132.4 1785.97  5152.4 1786.28
  5162.5 1786.14  5172.5 1786.52  5182.5 1786.32  5222.5 1786.65  5269.7 1787.81
  5274.7 1787.66  5302.7 1787.95  5322.7 1787.78  5372.8 1788.35  5409.3 1788.52
#Mann=4,-1,0
  4815.5    0.07       0  5035.9   0.045       0  5070.3    0.07       0
  5074.3   0.045       0
Bank Sta=5070.3,5074.3
Exp/Cntr=0.3,0.1

Type RM Length L Ch R = 1,1669,193,193,193
BEGIN DESCRIPTION:
Elm 01 34 1669.277
END DESCRIPTION:
XS GIS Cut Line= 3
      1547479.97      6842463.00      1547253.64      6842477.56
      1546819.35      6842461.00
#Sta/Elev= 30
  4773.2 1786.83  4778.5 1786.85  4788.2 1787.48  4808.2 1787.48  4818.3 1787.23
  4828.3 1786.07  4838.3 1785.37  4848.3 1785.54  4858.3 1785.06  4888.4 1785.07
  4918.5 1784.77  4931.2 1784.92  4938.5 1784.72  4948.5 1784.87  4994.8 1784.35
  4995.1 1783.85  4998.6 1783.85  4998.8 1784.35  5012.0 1784.42  5048.7 1784.73
  5078.7 1784.43  5116.7 1785.32  5148.7 1785.57  5158.8 1785.86  5168.8 1785.78
  5238.8 1786.43  5258.8 1786.84  5318.9 1787.29  5408.9 1788.42  5434.6 1788.44
#Mann=5,-1,0
  4773.2   0.035       0  4778.5    0.07       0  4994.8    0.07       0
  4998.8    0.07       0  5012.0   0.045       0
Bank Sta=4994.8,4998.8
Exp/Cntr=0.3,0.1

Type RM Length L Ch R = 1,1476,151,151,151
BEGIN DESCRIPTION:
Elm 01 34 1476.488
END DESCRIPTION:
XS GIS Cut Line= 3
      1547480.01      6842363.00      1547216.34      6842297.85
      1546852.46      6842310.50
#Sta/Elev= 30
  4728.4 1787.26  4743.9 1787.17  4754.2 1786.42  4764.5 1784.85  4769.8 1784.73
  4775.0 1784.98  4805.7 1784.44  4811.3 1784.62  4826.3 1784.38  4836.6 1784.55
  4894.2 1783.92  4929.3 1784.05  4943.1 1783.86  4991.1 1784.02  5009.3 1783.68
  5009.6 1783.18  5013.1 1783.18  5013.3 1783.68  5051.4 1784.22  5071.4 1784.20
  5081.4 1784.65  5091.4 1784.62  5121.4 1785.32  5131.4 1785.20  5161.4 1785.82
  5241.5 1786.55  5251.5 1786.93  5271.5 1786.93  5301.5 1787.43  5364.1 1787.97
#Mann=4,-1,0
  4728.4    0.07       0  4943.1   0.045       0  5009.3   0.045       0
  5013.3   0.045       0
Bank Sta=5009.3,5013.3
Exp/Cntr=0.3,0.1

Type RM Length L Ch R = 1,1325,215,215,215
BEGIN DESCRIPTION:
Elm 01 34 1325.096
END DESCRIPTION:
XS GIS Cut Line= 3
      1547529.99      6842213.00      1547303.40      6842181.95
      1546838.57      6842157.02
#Sta/Elev= 30
  4771.3 1786.87  4776.3 1787.54  4806.6 1787.14  4816.7 1785.64  4826.8 1784.74
  4843.4 1784.59  4857.1 1784.05  4867.2 1784.35  4897.5 1784.06  4907.5 1784.22
  4920.6 1783.84  4927.7 1784.05  4937.8 1783.76  4987.8 1783.60  4994.7 1783.33
  4994.9 1782.83  4998.4 1782.83  4998.7 1783.33  5008.4 1783.58  5021.3 1783.41
  5128.6 1783.62  5165.4 1784.13  5188.7 1784.08  5298.8 1785.92  5308.8 1785.84
  5328.9 1786.27  5378.9 1786.75  5389.0 1787.09  5449.0 1787.77  5465.5 1788.21
#Mann=4,-1,0
  4771.3    0.07       0  4994.7    0.07       0  4998.7    0.07       0
  5021.3   0.045       0
Bank Sta=4994.7,4998.7
Exp/Cntr=0.3,0.1

Type RM Length L Ch R = 1,1110,192,192,192
BEGIN DESCRIPTION:
Elm 01 34 1109.729
END DESCRIPTION:
XS GIS Cut Line= 3
      1547529.97      6842062.99      1547205.17      6842004.04
      1546868.94      6841997.28
#Sta/Elev= 30
  4669.9 1787.04  4674.9 1786.02  4685.1 1784.64  4695.3 1783.78  4705.4 1783.80
  4715.6 1783.30  4735.9 1783.19  4746.1 1782.83  4766.4 1783.04  4776.6 1782.73
  4807.1 1783.08  4932.3 1783.17  4947.0 1783.25  4952.1 1782.69  4959.5 1782.42
  4990.0 1782.84  5010.2 1782.81  5028.2 1782.38  5028.4 1781.88  5031.9 1781.88
  5032.2 1782.38  5053.4 1782.80  5070.2 1783.71  5100.2 1784.38  5240.2 1786.18
  5260.2 1786.64  5270.2 1786.52  5280.2 1787.02  5290.2 1786.93  5336.3 1787.62
#Mann=4,-1,0
  4669.9    0.07       0  4932.3   0.045       0  5028.2   0.045       0
  5032.2   0.045       0
Bank Sta=5028.2,5032.2
Exp/Cntr=0.3,0.1

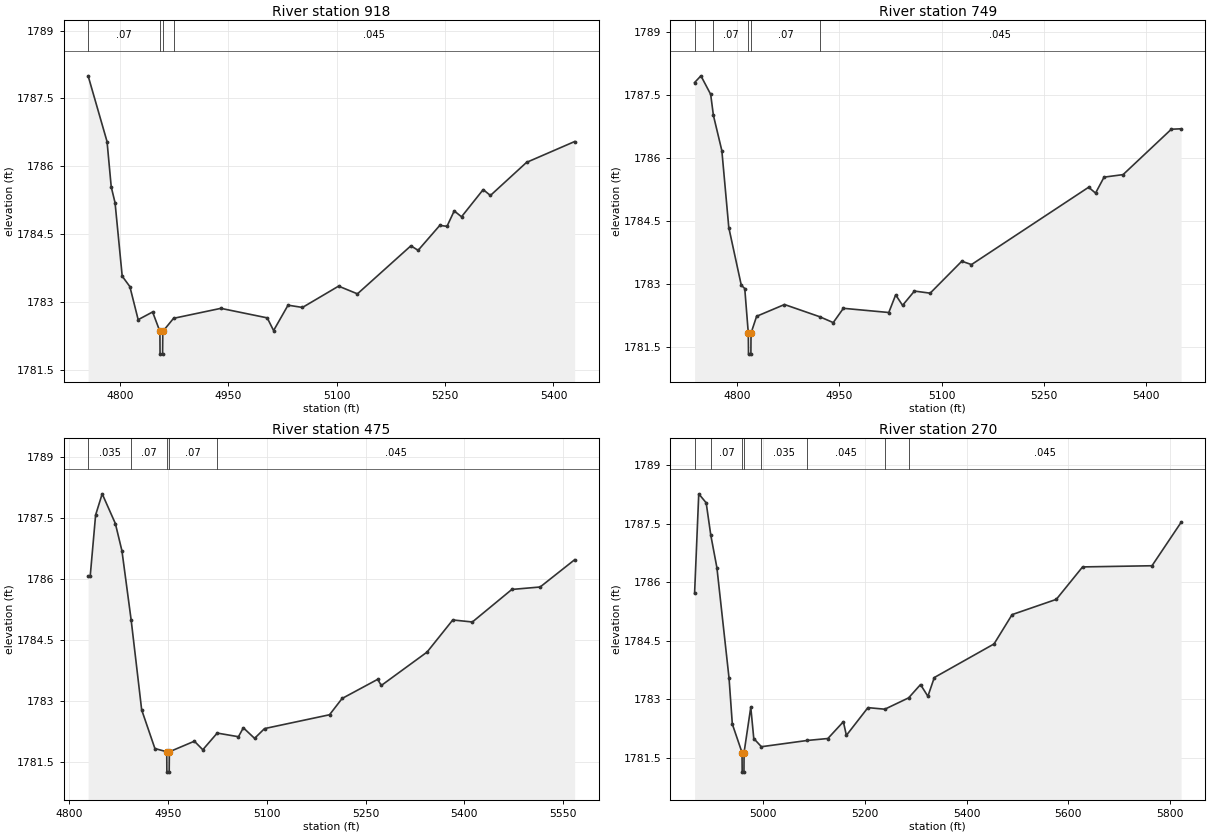
Type RM Length L Ch R = 1,918,169,169,169
BEGIN DESCRIPTION:
Elm 01 34 918.231
END DESCRIPTION:
XS GIS Cut Line= 3
      1547579.96      6841962.99      1547347.45      6841888.02
      1546918.47      6841871.40
#Sta/Elev= 30
  4755.7 1788.00  4781.9 1786.55  4787.7 1785.55  4793.0 1785.20  4802.9 1783.58
  4813.5 1783.35  4825.0 1782.62  4845.0 1782.79  4855.1 1782.36  4855.3 1781.86
  4858.8 1781.86  4859.1 1782.36  4874.0 1782.65  4939.5 1782.87  5003.7 1782.66
  5012.5 1782.38  5032.5 1782.94  5052.5 1782.89  5102.5 1783.36  5128.6 1783.19
  5202.6 1784.25  5212.6 1784.15  5242.6 1784.70  5252.6 1784.68  5262.6 1785.02
  5272.7 1784.89  5302.7 1785.49  5312.7 1785.36  5362.7 1786.09  5429.3 1786.55
#Mann=4,-1,0
  4755.7    0.07       0  4855.1   0.045       0  4859.1    0.07       0
  4874.0   0.045       0
Bank Sta=4855.1,4859.1
Exp/Cntr=0.3,0.1

Type RM Length L Ch R = 1,749,274,274,274
BEGIN DESCRIPTION:
Elm 01 34 749.092
END DESCRIPTION:
XS GIS Cut Line= 3
      1547614.11      6841797.65      1547357.38      6841743.87
      1546910.84      6841809.93
#Sta/Elev= 30
  4737.7 1787.80  4747.0 1787.96  4761.3 1787.52  4765.3 1787.02  4777.7 1786.18
  4787.9 1784.35  4806.2 1782.98  4811.3 1782.90  4816.5 1781.84  4816.8 1781.34
  4820.3 1781.34  4820.5 1781.84  4828.7 1782.24  4869.6 1782.52  4921.2 1782.23
  4941.1 1782.09  4956.0 1782.43  5022.6 1782.33  5032.7 1782.75  5042.8 1782.50
  5060.2 1782.84  5083.3 1782.79  5129.7 1783.55  5143.9 1783.47  5315.8 1785.31
  5325.9 1785.17  5338.4 1785.55  5366.3 1785.61  5437.1 1786.69  5451.4 1786.70
#Mann=5,-1,0
  4737.7   0.035       0  4765.3    0.07       0  4816.5   0.045       0
  4820.5    0.07       0  4921.2   0.045       0
Bank Sta=4816.5,4820.5
Exp/Cntr=0.3,0.1

Type RM Length L Ch R = 1,475,205,205,205
BEGIN DESCRIPTION:
Elm 01 34 474.635
END DESCRIPTION:
XS GIS Cut Line= 3
      1547626.41      6841558.10      1547454.78      6841563.00
      1546926.17      6841770.01
#Sta/Elev= 30
  4828.3 1786.07  4831.5 1786.07  4839.7 1787.57  4849.7 1788.09  4869.7 1787.36
  4879.7 1786.69  4893.7 1784.99  4909.7 1782.78  4929.8 1781.83  4947.8 1781.75
  4948.0 1781.25  4951.5 1781.25  4951.8 1781.75  4989.8 1782.01  5002.6 1781.80
  5024.5 1782.21  5056.8 1782.12  5064.2 1782.34  5081.3 1782.08  5096.4 1782.32
  5195.2 1782.66  5214.3 1783.06  5268.3 1783.53  5273.9 1783.38  5343.4 1784.20
  5382.5 1784.99  5412.3 1784.94  5472.3 1785.74  5515.3 1785.80  5567.7 1786.47
#Mann=5,-1,0
  4828.3   0.035       0  4893.7    0.07       0  4947.8    0.07       0
  4951.8    0.07       0  5024.5   0.045       0
Bank Sta=4947.8,4951.8
Exp/Cntr=0.3,0.1

Type RM Length L Ch R = 1,270,0,0,0
BEGIN DESCRIPTION:
Elm 01 34 269.734
END DESCRIPTION:
XS GIS Cut Line= 3
      1547561.89      6841312.43      1547448.64      6841385.72
      1546754.26      6841825.26
#Sta/Elev= 30
  4865.1 1785.71  4873.3 1788.26  4887.9 1788.03  4897.0 1787.20  4909.0 1786.37
  4932.9 1783.54  4939.3 1782.37  4958.4 1781.64  4958.7 1781.14  4962.2 1781.14
  4962.4 1781.64  4975.6 1782.80  4981.5 1782.00  4996.5 1781.79  5086.6 1781.95
  5127.2 1782.00  5157.7 1782.43  5163.6 1782.08  5206.0 1782.79  5239.2 1782.75
  5286.0 1783.04  5309.4 1783.38  5323.9 1783.08  5336.5 1783.56  5454.0 1784.42
  5489.5 1785.17  5576.4 1785.56  5628.1 1786.39  5764.6 1786.42  5821.8 1787.53
#Mann=8,-1,0
  4865.1   0.035       0  4897.0    0.07       0  4958.4   0.035       0
  4962.4    0.07       0  4996.5   0.035       0  5086.6   0.045       0
  5239.2    0.07       0  5286.0   0.045       0
Bank Sta=4958.4,4962.4
Exp/Cntr=0.3,0.1

Chan Stop Cuts=-1