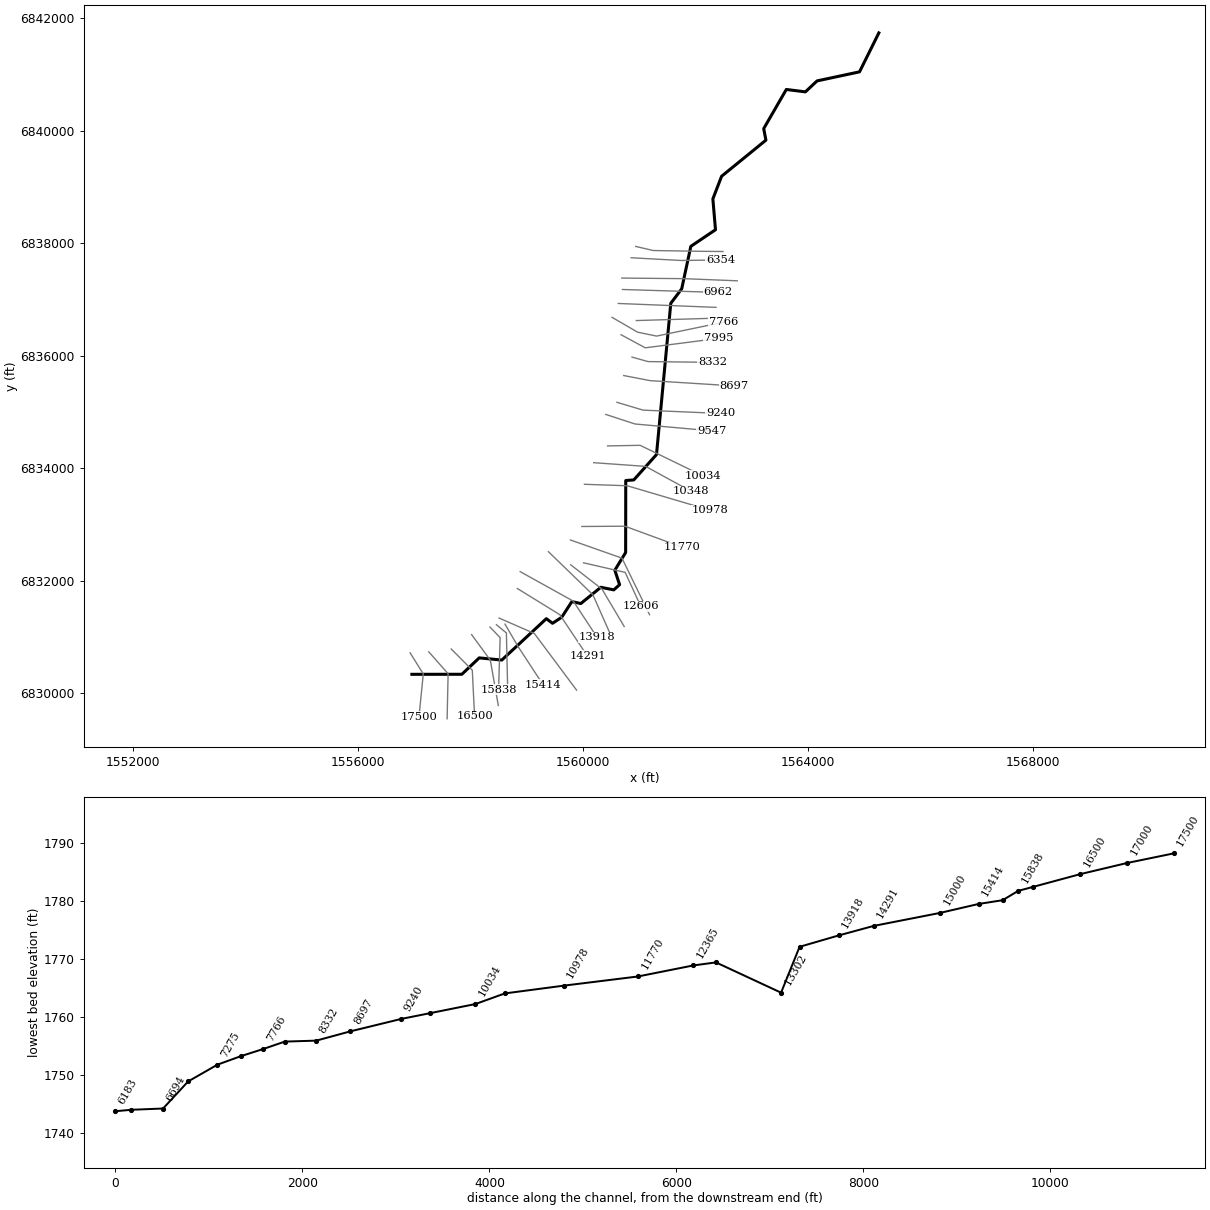
--- Elm 01 35.prj (project) ---

Proj Title=Elm 01 35 Base Level Engineering
Current Plan=p01
Default Exp/Contr=0.3,0.1
English Units
Geom File=g01
Flow File=f01
Plan File=p01
BEGIN DESCRIPTION:
Elm 01 35
END DESCRIPTION:

--- Elm 01 35.p01 (plan) ---

Plan Title=Multiple Run
Short Identifier=Multiple
Geom File=g01
Flow File=f01
Subcritical Flow
K Sum by GR= 0
Std Step Tol= 0.01
Critical Tol= 0.01
Num of Std Step Trials= 20
Max Error Tol= 0.3
Flow Tol Ratio= 0.001
Split Flow NTrial= 30
Split Flow Tol= 0.02
Split Flow Ratio= 0.02
Log Output Level= 0
Friction Slope Method= 1
Unsteady Friction Slope Method= 2
Unsteady Bridges Friction Slope Method= 1
Parabolic Critical Depth
Global Vel Dist=  1 , 1 , 1
Global Log Level= 0
CheckData=True
Encroach Param= -1, 0, 0, 0
BEGIN DESCRIPTION:
Multiple Run
END DESCRIPTION:

--- Elm 01 35.f01 (steady flow) ---

Flow Title=Multiple
Number of Profiles=7
Profile Names=10-year,25-year,50-year,1pct_min,100-year,1pct_plu,500-year
River Rch & RM= Elm 01 35,Reach-1,17500
     192     261     318     193     384     766     569
River Rch & RM= Elm 01 35,Reach-1,10978
     295     409     502     307     613    1223     924
River Rch & RM= Elm 01 35,Reach-1,4538
     457     644     800     494     985    1965    1514
Boundary for River Rch & Prof#=Elm 01 35,Reach-1,1
Up Type=0
Dn Type=3
Dn Slope=0.005
Boundary for River Rch & Prof#=Elm 01 35,Reach-1,2
Up Type=0
Dn Type=3
Dn Slope=0.005
Boundary for River Rch & Prof#=Elm 01 35,Reach-1,3
Up Type=0
Dn Type=3
Dn Slope=0.005
Boundary for River Rch & Prof#=Elm 01 35,Reach-1,4
Up Type=0
Dn Type=3
Dn Slope=0.005
Boundary for River Rch & Prof#=Elm 01 35,Reach-1,5
Up Type=0
Dn Type=3
Dn Slope=0.005
Boundary for River Rch & Prof#=Elm 01 35,Reach-1,6
Up Type=0
Dn Type=3
Dn Slope=0.005
Boundary for River Rch & Prof#=Elm 01 35,Reach-1,7
Up Type=0
Dn Type=3
Dn Slope=0.005

--- Elm 01 35.g01 (geometry) ---

Geom Title=Existing Conditions

River Reach=Elm 01 35,Reach-1
Reach XY= 30
      1556955.00      6830338.00      1557844.29      6830338.81
      1558151.65      6830630.02      1558553.54      6830591.54
      1559345.00      6831327.04      1559455.00      6831245.11
      1559618.24      6831351.62      1559798.54      6831630.36
      1559958.32      6831596.04      1560313.31      6831884.92
      1560544.39      6831838.59      1560647.20      6831931.79
      1560562.30      6832187.92      1560754.49      6832503.21
      1560756.65      6833782.35      1560899.36      6833792.84
      1561302.94      6834243.85      1561557.06      6836932.15
      1561751.24      6837189.56      1561913.02      6837944.34
      1562351.33      6838239.58      1562305.00      6838788.00
      1562460.41      6839190.71      1563247.64      6839831.66
      1563208.47      6840036.50      1563610.41      6840732.84
      1563949.55      6840690.16      1564156.63      6840884.87
      1564911.34      6841046.02      1565255.00      6841738.00

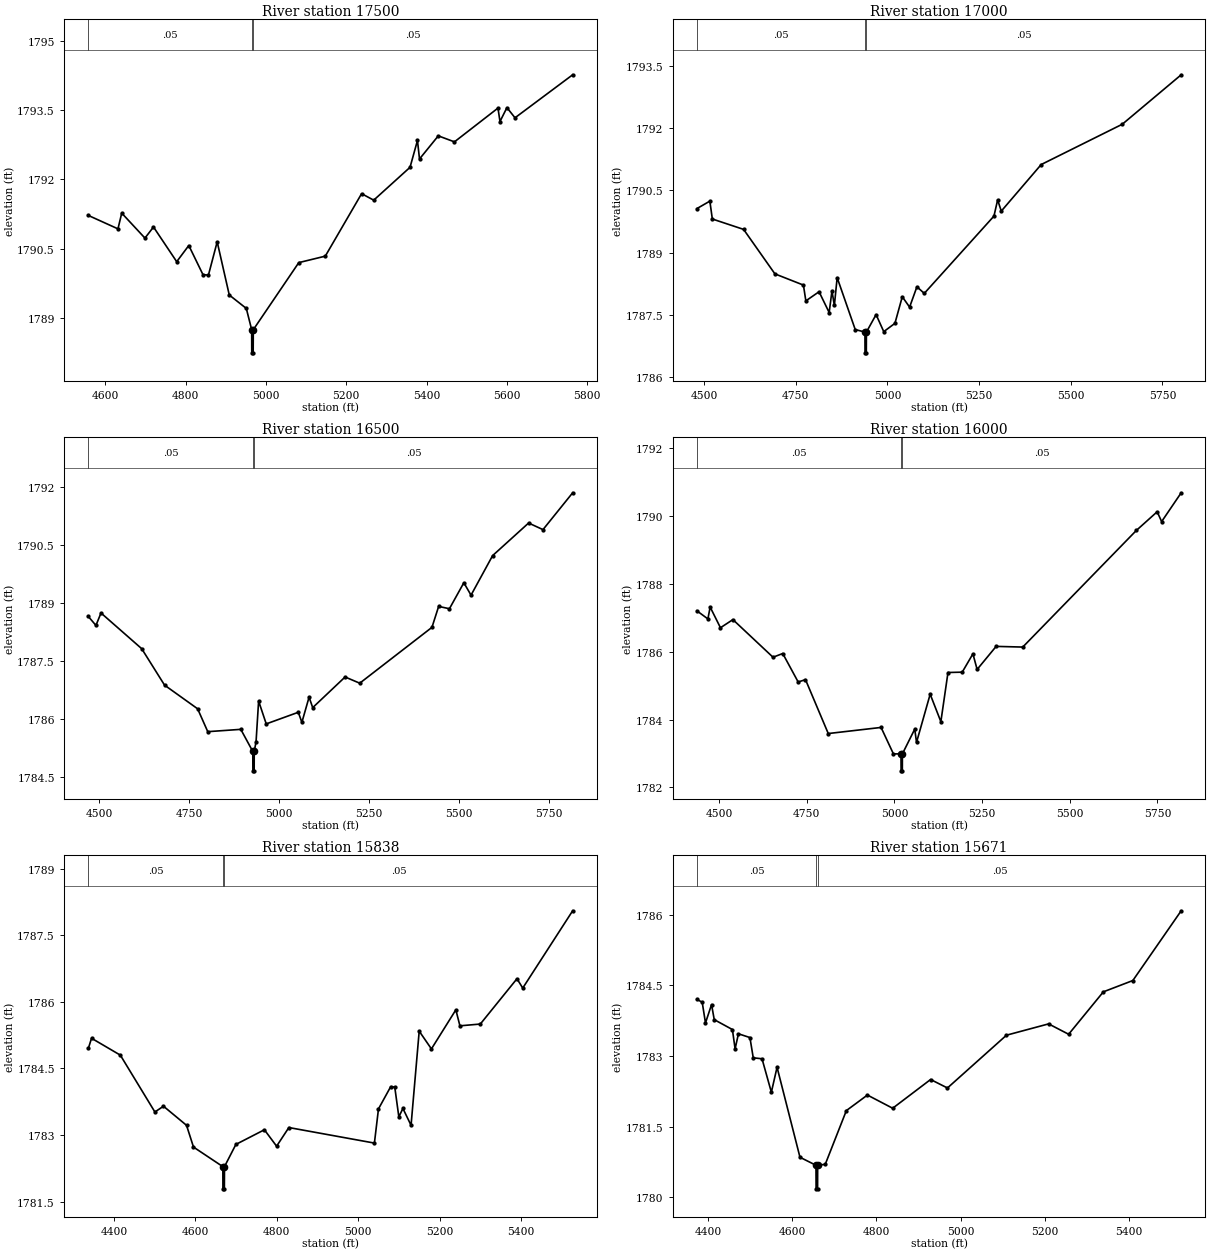
Type RM Length L Ch R = 1,17500,500,500,500
BEGIN DESCRIPTION:
Elm 01 35 35.0
END DESCRIPTION:
XS GIS Cut Line= 3
      1556923.76      6830720.17      1557158.10      6830344.94
      1557081.66      6829585.07
#Sta/Elev= 30
  4557.6 1791.22  4631.4 1790.93  4640.8 1791.27  4698.6 1790.73  4719.9 1790.97
  4777.7 1790.22  4807.8 1790.57  4843.1 1789.94  4856.7 1789.93  4878.5 1790.65
  4908.6 1789.50  4951.0 1789.21  4964.4 1788.75  4964.6 1788.25  4968.1 1788.25
  4968.4 1788.75  5081.7 1790.20  5147.7 1790.34  5238.1 1791.69  5268.3 1791.55
  5358.7 1792.26  5377.2 1792.84  5382.3 1792.44  5429.1 1792.94  5469.3 1792.81
  5577.7 1793.54  5582.7 1793.25  5600.0 1793.55  5620.1 1793.33  5763.7 1794.26
#Mann=3,-1,0
  4557.6    0.05       0  4964.4    0.05       0  4968.4    0.05       0
Bank Sta=4964.4,4968.4
Exp/Cntr=0.3,0.1

Type RM Length L Ch R = 1,17000,500,500,500
BEGIN DESCRIPTION:
Elm 01 35 34.0
END DESCRIPTION:
XS GIS Cut Line= 3
      1557255.02      6830737.98      1557599.32      6830348.29
      1557581.66      6829547.39
#Sta/Elev= 30
  4480.0 1790.06  4515.5 1790.24  4522.2 1789.81  4607.5 1789.56  4692.9 1788.49
  4770.7 1788.22  4777.3 1787.84  4813.3 1788.06  4840.9 1787.56  4848.5 1788.08
  4855.1 1787.73  4862.7 1788.40  4912.0 1787.15  4938.5 1787.09  4938.7 1786.59
  4942.2 1786.59  4942.5 1787.09  4968.9 1787.51  4989.8 1787.10  5020.3 1787.30
  5040.3 1787.94  5060.3 1787.69  5080.3 1788.18  5100.3 1788.02  5290.4 1789.88
  5300.4 1790.27  5310.4 1790.00  5419.2 1791.12  5640.4 1792.09  5801.1 1793.28
#Mann=3,-1,0
  4480.0    0.05       0  4938.5    0.05       0  4942.5    0.05       0
Bank Sta=4938.5,4942.5
Exp/Cntr=0.3,0.1

Type RM Length L Ch R = 1,16500,500,500,500
BEGIN DESCRIPTION:
Elm 01 35 33.0
END DESCRIPTION:
XS GIS Cut Line= 3
      1557655.00      6830788.00      1558029.10      6830411.15
      1558069.59      6829595.55
#Sta/Elev= 30
  4469.0 1788.65  4490.2 1788.42  4504.3 1788.74  4617.5 1787.82  4681.1 1786.88
  4773.1 1786.27  4801.3 1785.68  4893.2 1785.74  4926.6 1785.17  4926.9 1784.67
  4930.4 1784.67  4930.6 1785.17  4935.7 1785.42  4942.8 1786.47  4964.0 1785.88
  5053.2 1786.18  5063.2 1785.92  5083.2 1786.57  5093.3 1786.30  5183.4 1787.09
  5224.2 1786.93  5425.1 1788.37  5443.7 1788.91  5473.7 1788.85  5513.8 1789.52
  5533.8 1789.20  5593.9 1790.22  5694.0 1791.06  5734.0 1790.89  5816.6 1791.84
#Mann=3,-1,0
  4469.0    0.05       0  4926.6    0.05       0  4930.6    0.05       0
Bank Sta=4926.6,4930.6
Exp/Cntr=0.3,0.1

Type RM Length L Ch R = 1,16000,162,162,162
BEGIN DESCRIPTION:
Elm 01 35 32.0
END DESCRIPTION:
XS GIS Cut Line= 3
      1558017.51      6831043.46      1558349.65      6830588.50
      1558491.46      6829783.08
#Sta/Elev= 30
  4436.7 1787.21  4468.2 1786.97  4474.6 1787.32  4504.0 1786.71  4539.5 1786.95
  4653.9 1785.84  4681.6 1785.95  4725.6 1785.11  4746.5 1785.18  4811.4 1783.59
  4962.0 1783.77  4997.2 1782.99  5018.8 1782.99  5019.1 1782.49  5022.6 1782.49
  5022.8 1782.99  5058.0 1783.72  5063.1 1783.33  5102.0 1784.75  5132.5 1783.94
  5152.8 1785.39  5193.4 1785.40  5223.9 1785.94  5235.9 1785.48  5290.1 1786.16
  5366.0 1786.14  5690.0 1789.58  5749.3 1790.13  5762.0 1789.84  5817.8 1790.69
#Mann=3,-1,0
  4436.7    0.05       0  5018.8    0.05       0  5022.8    0.05       0
Bank Sta=5018.8,5022.8
Exp/Cntr=0.3,0.1

Type RM Length L Ch R = 1,15838,167,167,167
BEGIN DESCRIPTION:
Mapping XS 5c75288d
END DESCRIPTION:
XS GIS Cut Line= 3
      1558343.50      6831177.56      1558524.04      6830990.07
      1558496.32      6830061.27
#Sta/Elev= 30
  4337.1 1784.95  4345.0 1785.18  4415.7 1784.80  4500.6 1783.52  4521.7 1783.65
  4578.3 1783.22  4595.4 1782.73  4667.5 1782.29  4667.7 1781.79  4671.2 1781.79
  4671.5 1782.29  4699.5 1782.79  4769.5 1783.12  4799.5 1782.75  4829.6 1783.17
  5039.7 1782.82  5049.7 1783.59  5079.7 1784.09  5089.7 1784.08  5099.7 1783.41
  5109.7 1783.60  5129.7 1783.22  5149.7 1785.34  5179.7 1784.94  5239.7 1785.82
  5249.7 1785.46  5299.8 1785.50  5389.8 1786.52  5404.0 1786.31  5526.6 1788.05
#Mann=3,-1,0
  4337.1    0.05       0  4667.5    0.05       0  4671.5    0.05       0
Bank Sta=4667.5,4671.5
Exp/Cntr=0.3,0.1

Type RM Length L Ch R = 1,15671,257,257,257
BEGIN DESCRIPTION:
Mapping XS e3308046
END DESCRIPTION:
XS GIS Cut Line= 3
      1558458.06      6831219.25      1558635.15      6831073.41
      1558655.99      6830153.27
#Sta/Elev= 30
  4373.6 1784.20  4386.3 1784.14  4394.1 1783.70  4408.5 1784.09  4414.9 1783.77
  4458.0 1783.56  4464.4 1783.15  4472.3 1783.47  4499.6 1783.39  4507.5 1782.96
  4528.3 1782.94  4550.5 1782.23  4564.0 1782.76  4618.4 1780.85  4656.4 1780.68
  4656.7 1780.18  4660.2 1780.18  4660.4 1780.68  4678.4 1780.70  4728.5 1781.84
  4778.5 1782.17  4838.5 1781.89  4928.5 1782.50  4968.5 1782.32  5108.6 1783.44
  5208.6 1783.68  5256.2 1783.46  5338.6 1784.36  5408.6 1784.60  5523.4 1786.08
#Mann=3,-1,0
  4373.6    0.05       0  4656.4    0.05       0  4660.4    0.05       0
Bank Sta=4656.4,4660.4
Exp/Cntr=0.3,0.1

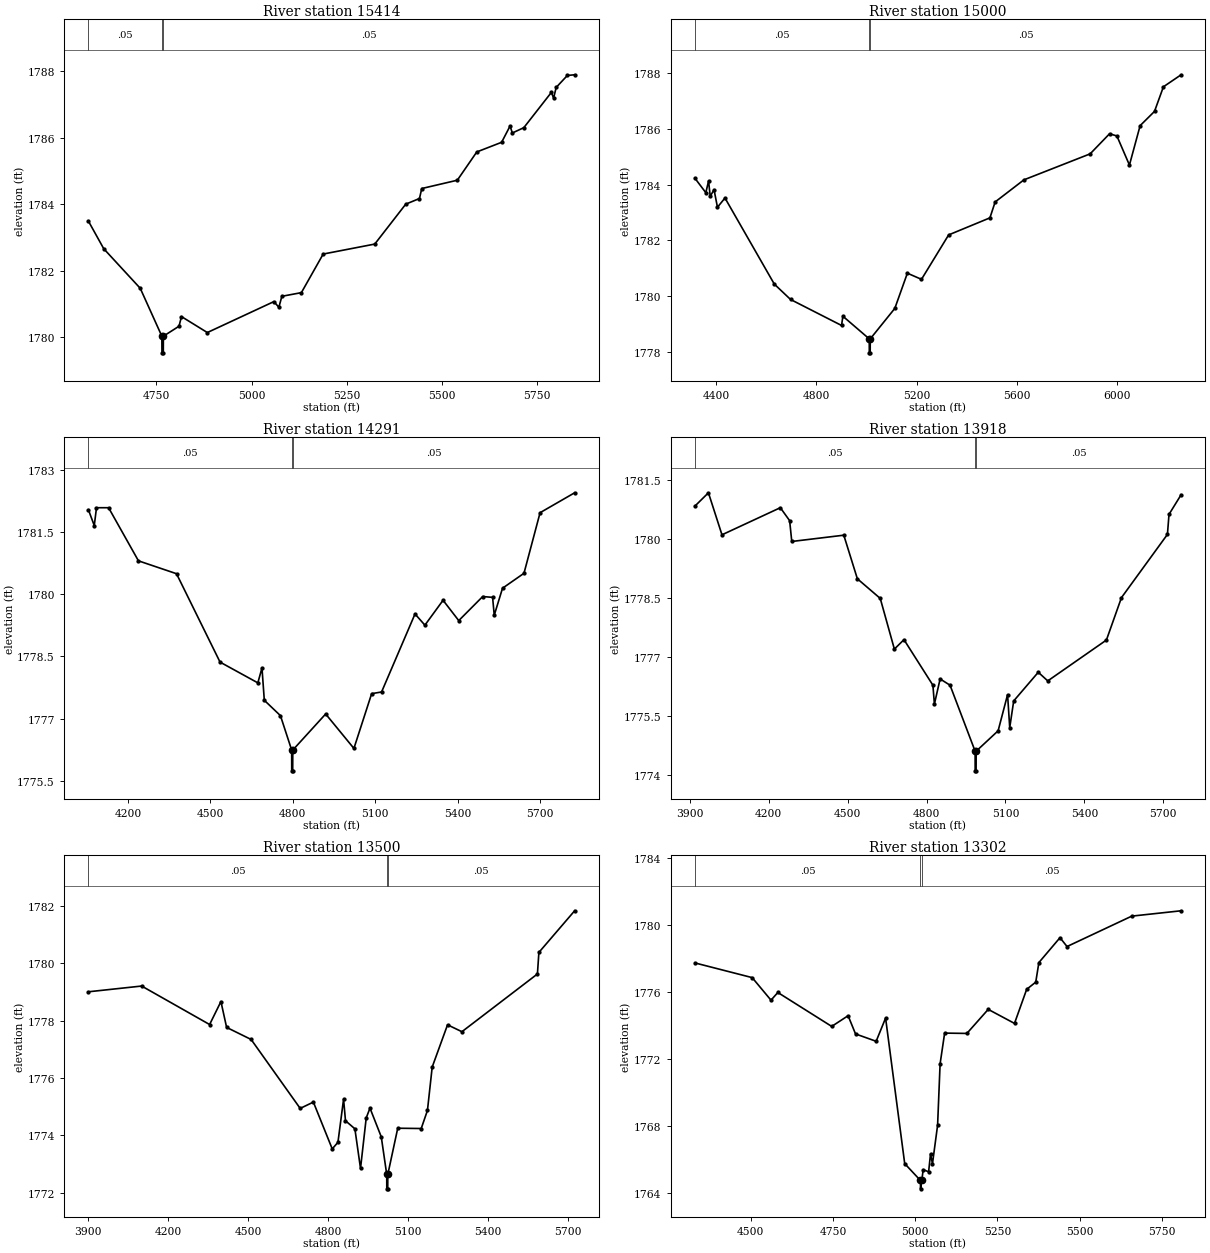
Type RM Length L Ch R = 1,15414,414,414,414
BEGIN DESCRIPTION:
Elm 01 35 31.0
END DESCRIPTION:
XS GIS Cut Line= 3
      1558610.85      6831229.66      1558836.54      6830840.77
      1559290.70      6830147.40
#Sta/Elev= 30
  4571.1 1783.49  4611.4 1782.66  4707.4 1781.47  4764.2 1780.03  4764.5 1779.53
  4768.0 1779.53  4768.2 1780.03  4809.3 1780.33  4815.8 1780.62  4883.8 1780.14
  5058.7 1781.07  5071.9 1780.90  5079.8 1781.23  5131.1 1781.34  5188.4 1782.50
  5324.0 1782.80  5405.5 1784.00  5441.6 1784.17  5447.6 1784.47  5541.1 1784.72
  5592.3 1785.57  5657.6 1785.86  5679.8 1786.35  5685.8 1786.14  5716.0 1786.30
  5788.4 1787.36  5794.3 1787.19  5801.1 1787.51  5830.5 1787.87  5849.6 1787.89
#Mann=3,-1,0
  4571.1    0.05       0  4764.2   0.035       0  4768.2    0.05       0
Bank Sta=4764.2,4768.2
Exp/Cntr=0.3,0.1

Type RM Length L Ch R = 1,15000,709,709,709
BEGIN DESCRIPTION:
Elm 01 35 30.0
END DESCRIPTION:
XS GIS Cut Line= 3
      1558504.99      6831338.00      1559132.11      6831063.66
      1559882.64      6830056.94
#Sta/Elev= 30
  4315.5 1784.23  4359.2 1783.71  4370.1 1784.13  4376.7 1783.58  4391.9 1783.82
  4405.6 1783.19  4435.6 1783.52  4632.4 1780.44  4697.2 1779.89  4900.7 1778.96
  4906.1 1779.29  5011.3 1778.48  5011.5 1777.98  5015.0 1777.98  5015.3 1778.48
  5113.3 1779.57  5163.4 1780.83  5219.7 1780.61  5328.1 1782.20  5492.8 1782.81
  5513.7 1783.38  5628.4 1784.17  5892.7 1785.10  5970.3 1785.82  5999.5 1785.74
  6049.5 1784.70  6092.2 1786.11  6149.6 1786.62  6185.1 1787.50  6255.7 1787.93
#Mann=3,-1,0
  4315.5    0.05       0  5011.3    0.05       0  5015.3    0.05       0
Bank Sta=5011.3,5015.3
Exp/Cntr=0.3,0.1

Type RM Length L Ch R = 1,14291,373,373,373
BEGIN DESCRIPTION:
Elm 01 35 29.0
END DESCRIPTION:
XS GIS Cut Line= 3
      1558829.96      6831863.02      1559585.21      6831397.64
      1560074.78      6830663.29
#Sta/Elev= 30
  4056.4 1782.03  4077.7 1781.65  4085.8 1782.08  4129.8 1782.08  4238.5 1780.80
  4377.0 1780.49  4535.5 1778.36  4673.1 1777.86  4688.1 1778.22  4696.6 1777.44
  4755.3 1777.07  4796.2 1776.24  4796.4 1775.74  4799.9 1775.74  4800.2 1776.24
  4919.9 1777.11  5022.7 1776.28  5087.3 1777.60  5123.4 1777.64  5245.1 1779.52
  5281.1 1779.25  5347.2 1779.85  5404.3 1779.36  5491.5 1779.94  5527.5 1779.92
  5533.5 1779.49  5563.6 1780.14  5641.7 1780.50  5700.3 1781.96  5826.1 1782.44
#Mann=3,-1,0
  4056.4    0.05       0  4796.2    0.05       0  4800.2    0.05       0
Bank Sta=4796.2,4800.2
Exp/Cntr=0.3,0.1

Type RM Length L Ch R = 1,13918,418,418,418
BEGIN DESCRIPTION:
Elm 01 35 28.0
END DESCRIPTION:
XS GIS Cut Line= 3
      1558879.98      6832163.01      1559824.95      6831638.25
      1560246.65      6830996.62
#Sta/Elev= 30
  3919.1 1780.84  3970.6 1781.18  4022.1 1780.11  4244.0 1780.80  4279.4 1780.47
  4287.5 1779.94  4485.3 1780.10  4536.9 1778.99  4623.9 1778.49  4677.6 1777.20
  4714.1 1777.44  4824.1 1776.28  4829.8 1775.80  4851.5 1776.44  4889.3 1776.28
  4984.6 1774.60  4984.8 1774.10  4988.3 1774.10  4988.6 1774.60  5072.1 1775.12
  5108.0 1776.04  5116.2 1775.20  5131.3 1775.88  5224.7 1776.61  5260.8 1776.39
  5483.8 1777.43  5541.0 1778.51  5715.8 1780.12  5721.8 1780.63  5767.8 1781.13
#Mann=3,-1,0
  3919.1    0.05       0  4984.6    0.05       0  4988.6    0.05       0
Bank Sta=4984.6,4988.6
Exp/Cntr=0.3,0.1

Type RM Length L Ch R = 1,13500,198,198,198
BEGIN DESCRIPTION:
Elm 01 35 27.0
END DESCRIPTION:
XS GIS Cut Line= 3
      1559382.07      6832517.45      1560171.77      6831753.28
      1560464.83      6831091.68
#Sta/Elev= 30
  3901.1 1779.00  4100.7 1779.20  4355.4 1777.86  4397.8 1778.66  4419.1 1777.76
  4511.0 1777.34  4694.9 1774.94  4744.3 1775.16  4815.0 1773.53  4836.4 1773.76
  4857.5 1775.26  4864.7 1774.51  4899.9 1774.23  4921.0 1772.85  4942.4 1774.61
  4956.5 1774.95  4998.8 1773.95  5019.3 1772.64  5019.5 1772.14  5023.0 1772.14
  5023.3 1772.64  5060.5 1774.25  5148.6 1774.24  5171.9 1774.87  5189.7 1776.38
  5247.2 1777.85  5301.1 1777.61  5584.1 1779.62  5589.6 1780.37  5723.6 1781.82
#Mann=3,-1,0
  3901.1    0.05       0  5019.3    0.05       0  5023.3    0.05       0
Bank Sta=5019.3,5023.3
Exp/Cntr=0.3,0.1

Type RM Length L Ch R = 1,13302,696,696,696
BEGIN DESCRIPTION:
Mapping XS 2b85c68f
END DESCRIPTION:
XS GIS Cut Line= 4
      1559777.51      6832285.22      1560215.02      6831944.94
      1560333.07      6831854.66      1560728.90      6831187.99
#Sta/Elev= 30
  4330.3 1777.75  4504.5 1776.87  4561.7 1775.52  4582.5 1775.98  4746.3 1773.95
  4796.1 1774.59  4818.7 1773.50  4881.4 1773.06  4910.1 1774.45  4968.2 1765.74
  5016.1 1764.73  5016.3 1764.23  5020.1 1764.73  5024.4 1765.38  5040.9 1765.25
  5046.7 1766.32  5052.6 1765.73  5068.2 1768.04  5075.8 1771.71  5089.6 1773.55
  5157.2 1773.53  5222.1 1774.97  5302.0 1774.13  5339.0 1776.17  5366.6 1776.60
  5376.1 1777.77  5440.3 1779.26  5461.7 1778.73  5658.5 1780.55  5808.5 1780.87
#Mann=3,-1,0
  4330.3    0.05       0  5016.1    0.05       0  5020.1    0.05       0
Bank Sta=5016.1,5020.1
Exp/Cntr=0.3,0.1

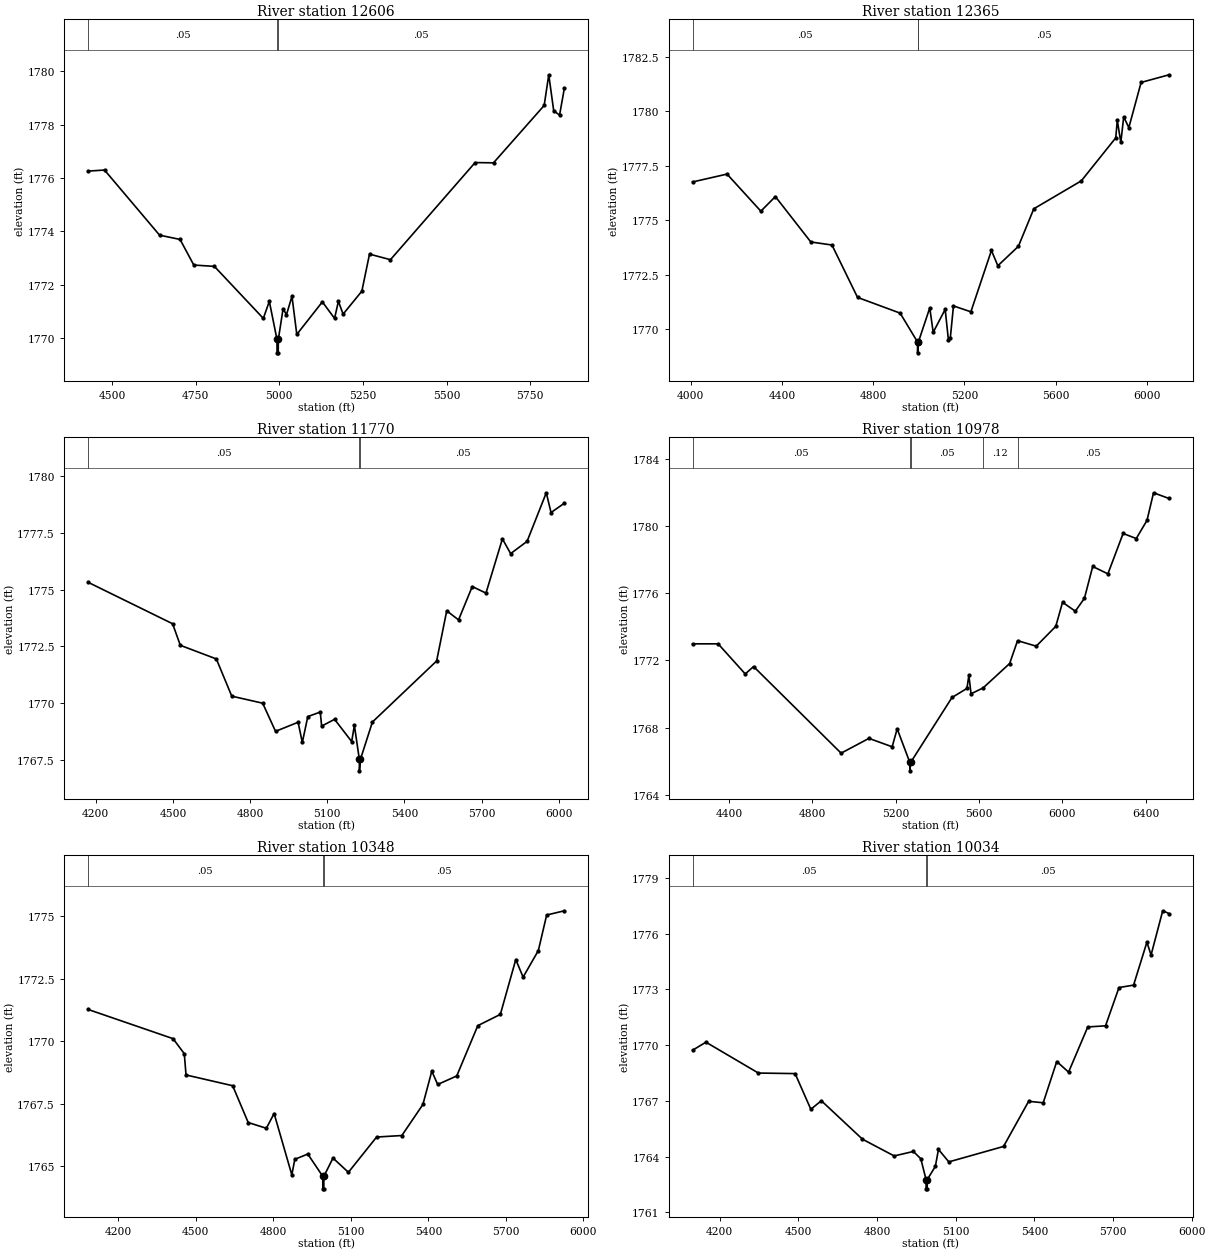
Type RM Length L Ch R = 1,12606,241,241,241
BEGIN DESCRIPTION:
Mapping XS 4d3d8e7d
END DESCRIPTION:
XS GIS Cut Line= 3
      1560006.69      6832319.93      1560746.27      6832149.80
      1561024.06      6831545.59
#Sta/Elev= 30
  4428.3 1776.26  4477.9 1776.30  4642.4 1773.86  4703.6 1773.70  4744.7 1772.74
  4806.2 1772.69  4952.5 1770.74  4970.4 1771.38  4993.3 1769.95  4993.5 1769.45
  4997.0 1769.45  4997.3 1769.95  5011.5 1771.10  5021.7 1770.88  5038.1 1771.57
  5052.5 1770.14  5128.9 1771.36  5165.4 1770.74  5176.8 1771.38  5190.9 1770.90
  5246.9 1771.76  5269.8 1773.15  5332.3 1772.94  5585.4 1776.58  5640.4 1776.57
  5791.8 1778.72  5805.5 1779.87  5820.3 1778.52  5837.8 1778.36  5852.2 1779.37
#Mann=3,-1,0
  4428.3    0.05       0  4993.3    0.05       0  4997.3    0.05       0
Bank Sta=4993.3,4997.3
Exp/Cntr=0.3,0.1

Type RM Length L Ch R = 1,12365,595,595,595
BEGIN DESCRIPTION:
Mapping XS d97c54f3
END DESCRIPTION:
XS GIS Cut Line= 3
      1559772.67      6832725.78      1560689.38      6832402.85
      1561178.96      6831397.65
#Sta/Elev= 30
  4007.9 1776.76  4158.8 1777.12  4307.2 1775.42  4370.8 1776.09  4526.2 1774.01
  4619.1 1773.87  4731.3 1771.47  4918.0 1770.75  4994.3 1769.43  4994.6 1768.93
  4998.3 1769.43  5048.1 1770.99  5063.1 1769.87  5115.7 1770.92  5129.8 1769.53
  5138.2 1769.61  5152.1 1771.08  5228.4 1770.81  5318.6 1773.62  5346.7 1772.92
  5436.8 1773.81  5504.5 1775.53  5712.9 1776.81  5863.9 1778.78  5870.7 1779.58
  5886.2 1778.57  5898.8 1779.74  5921.3 1779.25  5975.2 1781.32  6097.9 1781.67
#Mann=3,-1,0
  4007.9    0.05       0  4994.3    0.05       0  4998.3    0.05       0
Bank Sta=4994.3,4998.3
Exp/Cntr=0.3,0.1

Type RM Length L Ch R = 1,11770,792,792,792
BEGIN DESCRIPTION:
Mapping XS 27f1bca0
END DESCRIPTION:
XS GIS Cut Line= 3
      1559975.86      6832965.35      1560741.46      6832970.55
      1561761.12      6832595.98
#Sta/Elev= 30
  4169.7 1775.33  4498.8 1773.50  4528.8 1772.55  4668.8 1771.95  4728.8 1770.31
  4848.9 1770.00  4898.9 1768.76  4986.6 1769.16  5003.0 1768.27  5024.3 1769.41
  5072.7 1769.61  5078.1 1768.99  5128.4 1769.29  5194.8 1768.31  5205.4 1769.02
  5224.7 1767.52  5225.0 1767.02  5228.7 1767.52  5275.4 1769.17  5525.0 1771.86
  5564.3 1774.07  5610.2 1773.67  5663.5 1775.14  5716.8 1774.85  5780.7 1777.24
  5812.7 1776.59  5876.6 1777.13  5951.2 1779.27  5969.7 1778.40  6021.6 1778.81
#Mann=3,-1,0
  4169.7    0.05       0  5224.7    0.05       0  5228.7    0.05       0
Bank Sta=5224.7,5228.7
Exp/Cntr=0.3,0.1

Type RM Length L Ch R = 1,10978,630,630,630
BEGIN DESCRIPTION:
Mapping XS 90d4a898
END DESCRIPTION:
XS GIS Cut Line= 3
      1560022.68      6833715.35      1560783.13      6833689.30
      1562246.63      6833257.02
#Sta/Elev= 30
  4225.7 1772.99  4348.1 1772.99  4478.2 1771.20  4518.2 1771.64  4938.4 1766.49
  5072.0 1767.37  5183.4 1766.87  5207.5 1767.94  5268.1 1765.94  5268.3 1765.44
  5272.1 1765.94  5470.6 1769.80  5542.4 1770.34  5551.6 1771.12  5562.0 1770.02
  5620.0 1770.37  5747.3 1771.82  5785.3 1773.18  5874.8 1772.85  5968.7 1774.03
  6001.2 1775.46  6062.5 1774.93  6106.3 1775.70  6146.0 1777.59  6218.9 1777.15
  6291.9 1779.55  6355.0 1779.25  6406.6 1780.33  6437.9 1781.97  6512.6 1781.63
#Mann=5,-1,0
  4225.7    0.05       0  5268.1    0.05       0  5272.1    0.05       0
  5620.0    0.12       0  5785.3    0.05       0
Bank Sta=5268.1,5272.1
Exp/Cntr=0.3,0.1

Type RM Length L Ch R = 1,10348,314,314,314
BEGIN DESCRIPTION:
Mapping XS 1e511f6c
END DESCRIPTION:
XS GIS Cut Line= 3
      1560186.37      6834099.45      1561109.98      6834033.48
      1561915.08      6833592.75
#Sta/Elev= 30
  4082.5 1771.27  4412.0 1770.10  4455.4 1769.50  4462.1 1768.65  4642.6 1768.22
  4702.7 1766.75  4772.9 1766.52  4803.0 1767.11  4871.5 1764.66  4883.2 1765.28
  4933.3 1765.49  4991.3 1764.60  4991.6 1764.10  4995.3 1764.10  4995.6 1764.60
  5030.8 1765.33  5090.5 1764.76  5199.6 1766.17  5297.3 1766.23  5378.8 1767.47
  5413.2 1768.80  5436.0 1768.27  5509.7 1768.61  5591.2 1770.62  5678.5 1771.07
  5738.2 1773.26  5766.6 1772.56  5825.5 1773.62  5857.7 1775.04  5926.3 1775.21
#Mann=3,-1,0
  4082.5    0.05       0  4991.3    0.05       0  4995.6    0.05       0
Bank Sta=4991.3,4995.6
Exp/Cntr=0.3,0.1

Type RM Length L Ch R = 1,10034,487,487,487
BEGIN DESCRIPTION:
Mapping XS e947894f
END DESCRIPTION:
XS GIS Cut Line= 3
      1560434.20      6834397.64      1561012.30      6834408.05
      1562126.86      6833866.40
#Sta/Elev= 30
  4096.5 1769.73  4147.3 1770.16  4347.3 1768.50  4487.4 1768.47  4547.4 1766.55
  4587.4 1767.01  4744.4 1764.94  4865.2 1764.04  4938.4 1764.28  4966.8 1763.89
  4986.8 1762.77  4987.1 1762.27  4991.1 1762.27  4991.5 1762.77  5022.4 1763.48
  5034.2 1764.39  5073.8 1763.72  5282.4 1764.55  5378.2 1766.98  5433.7 1766.90
  5485.4 1769.12  5530.5 1768.55  5603.7 1770.98  5671.4 1771.04  5722.8 1773.10
  5778.4 1773.23  5829.3 1775.54  5845.1 1774.85  5889.6 1777.23  5913.9 1777.08
#Mann=3,-1,0
  4096.5    0.05       0  4986.8    0.05       0  4991.5    0.05       0
Bank Sta=4986.8,4991.5
Exp/Cntr=0.3,0.1

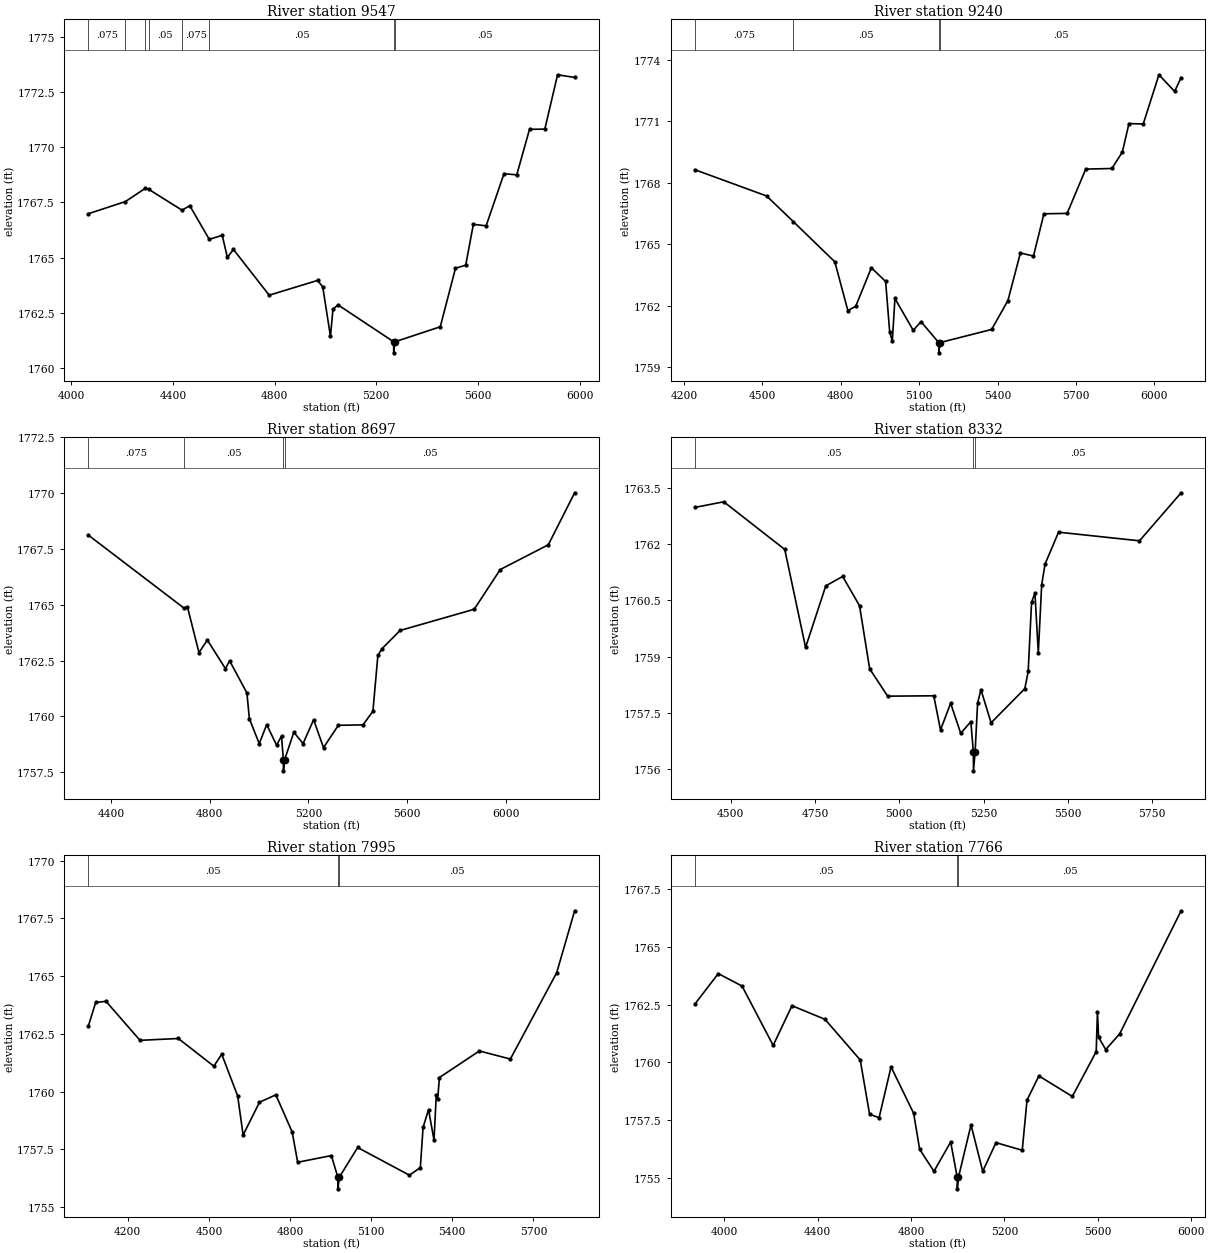
Type RM Length L Ch R = 1,9547,307,307,307
BEGIN DESCRIPTION:
Mapping XS ef86ae5e
END DESCRIPTION:
XS GIS Cut Line= 3
      1560401.63      6834957.09      1560922.48      6834786.95
      1562281.84      6834665.58
#Sta/Elev= 30
  4067.8 1766.99  4213.5 1767.54  4291.7 1768.14  4304.3 1768.10  4435.8 1767.15
  4466.6 1767.35  4543.2 1765.83  4594.2 1766.01  4614.4 1765.01  4638.3 1765.37
  4778.9 1763.30  4969.7 1763.97  4989.7 1763.67  5019.9 1761.44  5029.9 1762.67
  5050.0 1762.86  5268.5 1761.19  5268.8 1760.69  5273.3 1761.19  5451.9 1761.87
  5511.8 1764.52  5552.0 1764.66  5582.1 1766.51  5632.3 1766.44  5702.6 1768.80
  5752.8 1768.75  5803.0 1770.81  5863.2 1770.82  5913.4 1773.28  5980.5 1773.16
#Mann=8,-1,0
  4067.8   0.075       0  4213.5    0.05       0  4291.7   0.075       0
  4304.3    0.05       0  4435.8   0.075       0  4543.2    0.05       0
  5268.5    0.05       0  5273.3    0.05       0
Bank Sta=5268.5,5273.3
Exp/Cntr=0.3,0.1

Type RM Length L Ch R = 1,9240,543,543,543
BEGIN DESCRIPTION:
Mapping XS f19478f4
END DESCRIPTION:
XS GIS Cut Line= 3
      1560599.58      6835172.36      1561064.84      6835033.48
      1562439.83      6834974.45
#Sta/Elev= 30
  4241.1 1768.63  4515.7 1767.35  4618.0 1766.10  4776.9 1764.14  4826.9 1761.76
  4856.9 1761.97  4917.0 1763.85  4971.5 1763.18  4987.0 1760.72  4997.1 1760.27
  5007.1 1762.35  5077.1 1760.80  5107.2 1761.22  5174.8 1760.20  5175.1 1759.70
  5179.7 1760.20  5377.4 1760.84  5439.8 1762.25  5487.5 1764.57  5537.6 1764.42
  5577.6 1766.48  5666.5 1766.50  5737.7 1768.66  5837.8 1768.69  5877.9 1769.49
  5903.2 1770.88  5957.9 1770.86  6018.0 1773.26  6078.0 1772.45  6102.9 1773.12
#Mann=4,-1,0
  4241.1   0.075       0  4618.0    0.05       0  5174.8    0.03       0
  5179.7    0.05       0
Bank Sta=5174.8,5179.7
Exp/Cntr=0.3,0.1

Type RM Length L Ch R = 1,8697,365,365,365
BEGIN DESCRIPTION:
Mapping XS 6bb71c7e
END DESCRIPTION:
XS GIS Cut Line= 3
      1560721.12      6835648.05      1561189.84      6835557.78
      1562681.47      6835464.12
#Sta/Elev= 30
  4307.7 1768.12  4695.6 1764.85  4709.2 1764.91  4756.0 1762.86  4790.2 1763.42
  4863.3 1762.14  4880.4 1762.49  4950.5 1761.05  4960.5 1759.89  5000.6 1758.78
  5030.7 1759.63  5070.8 1758.71  5090.8 1759.12  5098.2 1758.06  5098.6 1757.56
  5103.4 1758.06  5140.9 1759.29  5178.2 1758.78  5221.0 1759.85  5261.1 1758.60
  5321.2 1759.60  5421.4 1759.62  5461.5 1760.23  5481.6 1762.73  5498.1 1763.03
  5571.7 1763.85  5872.3 1764.80  5977.9 1766.58  6172.9 1767.69  6279.6 1770.02
#Mann=4,-1,0
  4307.7   0.075       0  4695.6    0.05       0  5098.2    0.03       0
  5103.4    0.05       0
Bank Sta=5098.2,5103.4
Exp/Cntr=0.3,0.1

Type RM Length L Ch R = 1,8332,337,337,337
BEGIN DESCRIPTION:
Mapping XS 28a72587
END DESCRIPTION:
XS GIS Cut Line= 3
      1560867.76      6835976.19      1561152.52      6835896.32
      1562298.39      6835882.43
#Sta/Elev= 30
  4393.7 1762.98  4479.3 1763.13  4660.2 1761.86  4721.9 1759.25  4781.9 1760.89
  4831.9 1761.14  4881.9 1760.36  4911.9 1758.68  4965.3 1757.95  5102.0 1757.96
  5122.0 1757.05  5152.0 1757.76  5182.0 1756.96  5212.0 1757.27  5219.4 1756.46
  5219.8 1755.96  5224.6 1756.46  5232.0 1757.77  5242.0 1758.12  5272.0 1757.24
  5372.0 1758.15  5382.0 1758.61  5392.0 1760.45  5402.0 1760.70  5412.0 1759.10
  5422.0 1760.92  5432.0 1761.47  5472.0 1762.32  5712.0 1762.09  5835.4 1763.37
#Mann=3,-1,0
  4393.7    0.05       0  5219.4    0.03       0  5224.6    0.05       0
Bank Sta=5219.4,5224.6
Exp/Cntr=0.3,0.1

Type RM Length L Ch R = 1,7995,229,229,229
BEGIN DESCRIPTION:
Mapping XS d5fcc14b
END DESCRIPTION:
XS GIS Cut Line= 3
      1560672.48      6836373.75      1561103.04      6836141.12
      1562400.81      6836307.67
#Sta/Elev= 30
  4054.5 1762.85  4081.4 1763.86  4119.5 1763.91  4245.2 1762.22  4387.0 1762.30
  4518.3 1761.10  4547.4 1761.62  4606.4 1759.81  4626.5 1758.12  4687.0 1759.54
  4747.5 1759.86  4808.0 1758.25  4828.2 1756.94  4952.8 1757.23  4976.8 1756.29
  4977.2 1755.79  4982.0 1756.29  5050.0 1757.58  5241.5 1756.38  5281.8 1756.71
  5291.9 1758.45  5312.1 1759.22  5332.3 1757.90  5340.8 1759.87  5345.8 1759.67
  5352.4 1760.61  5500.0 1761.76  5614.6 1761.41  5786.0 1765.15  5852.3 1767.83
#Mann=3,-1,0
  4054.5    0.05       0  4976.8    0.05       0  4982.0    0.05       0
Bank Sta=4976.8,4982
Exp/Cntr=0.3,0.1

Type RM Length L Ch R = 1,7766,242,242,242
BEGIN DESCRIPTION:
Mapping XS 9d8d7609
END DESCRIPTION:
XS GIS Cut Line= 4
      1560512.73      6836682.80      1560967.62      6836418.89
      1561304.43      6836349.45      1562490.93      6836595.77
#Sta/Elev= 30
  3874.5 1762.52  3974.6 1763.84  4076.4 1763.30  4209.7 1760.73  4290.1 1762.45
  4431.5 1761.86  4582.4 1760.10  4622.4 1757.75  4663.2 1757.60  4714.3 1759.80
  4811.1 1757.79  4836.8 1756.23  4898.1 1755.28  4969.6 1756.55  4997.6 1755.02
  4998.0 1754.52  5002.9 1755.02  5056.7 1757.29  5106.8 1755.28  5163.6 1756.52
  5276.0 1756.19  5296.4 1758.36  5347.2 1759.41  5490.4 1758.52  5592.6 1760.46
  5597.9 1762.18  5603.0 1761.08  5633.4 1760.55  5693.0 1761.23  5956.1 1766.56
#Mann=3,-1,0
  3874.5    0.05       0  4997.6    0.03       0  5002.9    0.05       0
Bank Sta=4997.6,5002.9
Exp/Cntr=0.3,0.1

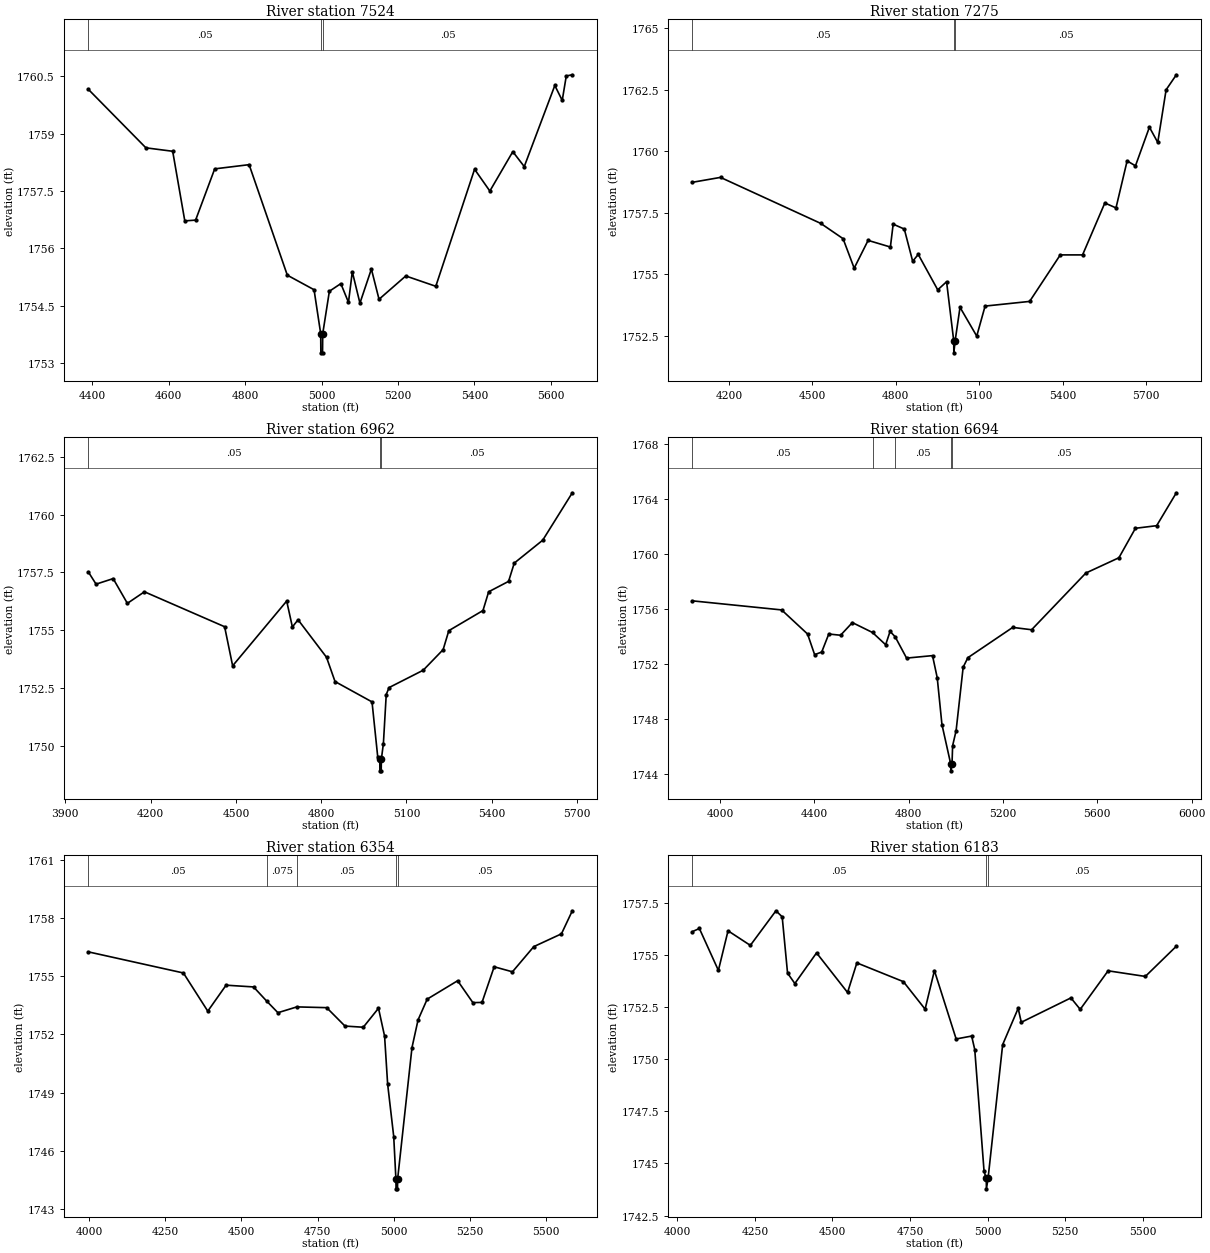
Type RM Length L Ch R = 1,7524,249,249,249
BEGIN DESCRIPTION:
Mapping XS f78fc61f
END DESCRIPTION:
XS GIS Cut Line= 2
      1560944.23      6836625.49      1562210.76      6836663.66
#Sta/Elev= 30
  4389.3 1760.16  4540.1 1758.63  4610.2 1758.54  4641.9 1756.72  4670.2 1756.74
  4720.2 1758.08  4810.3 1758.19  4910.3 1755.30  4980.3 1754.92  4997.7 1753.77
  4998.1 1753.27  5002.5 1753.27  5003.0 1753.77  5020.4 1754.88  5050.4 1755.08
  5070.4 1754.59  5080.4 1755.39  5100.4 1754.57  5130.4 1755.46  5150.4 1754.67
  5220.4 1755.28  5299.0 1755.01  5400.5 1758.07  5440.5 1757.50  5500.6 1758.53
  5530.6 1758.14  5610.6 1760.26  5630.0 1759.87  5640.6 1760.51  5656.4 1760.54
#Mann=3,-1,0
  4389.3    0.05       0  4997.7    0.05       0  5003.0    0.05       0
Bank Sta=4997.7,5003
Exp/Cntr=0.3,0.1

Type RM Length L Ch R = 1,7275,313,313,313
BEGIN DESCRIPTION:
Mapping XS 16c0b7a9
END DESCRIPTION:
XS GIS Cut Line= 2
      1560623.86      6836929.31      1562361.77      6836859.93
#Sta/Elev= 30
  4068.6 1758.74  4169.8 1758.94  4530.1 1757.07  4610.2 1756.45  4650.2 1755.25
  4700.2 1756.38  4780.3 1756.11  4790.3 1757.04  4830.3 1756.84  4860.4 1755.53
  4880.4 1755.81  4950.4 1754.37  4982.2 1754.70  5007.8 1752.31  5008.3 1751.81
  5013.1 1752.31  5030.5 1753.66  5090.6 1752.49  5120.6 1753.71  5280.7 1753.90
  5390.8 1755.79  5470.9 1755.79  5550.9 1757.90  5591.0 1757.70  5631.0 1759.61
  5661.0 1759.41  5711.1 1760.98  5741.1 1760.36  5771.1 1762.50  5807.9 1763.11
#Mann=3,-1,0
  4068.6    0.05       0  5007.8    0.05       0  5013.1    0.05       0
Bank Sta=5007.8,5013.1
Exp/Cntr=0.3,0.1

Type RM Length L Ch R = 1,6962,268,268,268
BEGIN DESCRIPTION:
Mapping XS 38f1c906
END DESCRIPTION:
XS GIS Cut Line= 2
      1560697.67      6837177.57      1562399.08      6837125.49
#Sta/Elev= 30
  3981.0 1757.52  4008.3 1756.99  4068.4 1757.23  4118.4 1756.16  4178.4 1756.66
  4460.4 1755.15  4488.6 1753.46  4678.7 1756.26  4698.7 1755.14  4718.7 1755.45
  4818.7 1753.83  4848.7 1752.78  4978.8 1751.90  4998.8 1749.53  5006.1 1749.42
  5006.5 1748.92  5011.1 1748.92  5011.6 1749.42  5018.8 1750.10  5028.8 1752.22
  5038.8 1752.52  5158.9 1753.27  5228.9 1754.16  5248.9 1754.98  5369.0 1755.85
  5389.0 1756.66  5459.0 1757.11  5479.0 1757.90  5579.1 1758.89  5683.2 1760.94
#Mann=3,-1,0
  3981.0    0.05       0  5006.1    0.05       0  5011.6    0.05       0
Bank Sta=5006.1,5011.6
Exp/Cntr=0.3,0.1

Type RM Length L Ch R = 1,6694,340,340,340
BEGIN DESCRIPTION:
Mapping XS 51caf6b7
END DESCRIPTION:
XS GIS Cut Line= 3
      1560686.36      6837380.70      1561790.54      6837370.28
      1562738.45      6837332.09
#Sta/Elev= 30
  3882.2 1756.60  4260.9 1755.94  4370.9 1754.19  4400.9 1752.69  4430.9 1752.88
  4460.9 1754.19  4510.9 1754.10  4560.9 1755.02  4646.4 1754.30  4702.1 1753.41
  4720.9 1754.38  4742.4 1753.99  4790.9 1752.44  4900.9 1752.62  4920.9 1751.01
  4940.9 1747.61  4978.1 1744.75  4978.6 1744.25  4983.6 1744.75  4986.2 1746.08
  5000.9 1747.16  5030.9 1751.78  5050.9 1752.47  5241.1 1754.67  5321.2 1754.50
  5551.3 1758.62  5691.5 1759.73  5761.5 1761.87  5851.6 1762.06  5935.1 1764.45
#Mann=5,-1,0
  3882.2    0.05       0  4646.4   0.075       0  4742.4    0.05       0
  4978.1    0.03       0  4983.6    0.05       0
Bank Sta=4978.1,4983.6
Exp/Cntr=0.3,0.1

Type RM Length L Ch R = 1,6354,171,171,171
BEGIN DESCRIPTION:
Mapping XS 8b2eab68
END DESCRIPTION:
XS GIS Cut Line= 3
      1560853.04      6837741.81      1561741.93      6837693.20
      1562441.63      6837703.59
#Sta/Elev= 30
  3996.9 1756.26  4309.3 1755.17  4389.4 1753.20  4449.5 1754.54  4539.7 1754.45
  4582.8 1753.72  4619.8 1753.12  4682.1 1753.42  4780.0 1753.38  4840.1 1752.43
  4900.2 1752.37  4950.2 1753.35  4970.2 1751.91  4980.2 1749.44  5000.2 1746.73
  5007.4 1744.53  5007.9 1744.03  5012.6 1744.03  5013.0 1744.53  5060.2 1751.32
  5080.2 1752.75  5110.2 1753.82  5210.2 1754.77  5260.2 1753.64  5290.2 1753.65
  5330.2 1755.49  5390.2 1755.23  5460.3 1756.53  5551.2 1757.19  5586.9 1758.38
#Mann=5,-1,0
  3996.9    0.05       0  4582.8   0.075       0  4682.1    0.05       0
  5007.4    0.03       0  5013.0    0.05       0
Bank Sta=5007.4,5013
Exp/Cntr=0.3,0.1

Type RM Length L Ch R = 1,6183,287,287,287
BEGIN DESCRIPTION:
Mapping XS a76ea9fb
END DESCRIPTION:
XS GIS Cut Line= 4
      1560932.92      6837943.19      1561245.40      6837870.28
      1562089.15      6837856.39      1562484.99      6837852.92
#Sta/Elev= 30
  4048.3 1756.12  4071.0 1756.27  4132.3 1754.26  4163.4 1756.16  4235.3 1755.46
  4317.9 1757.12  4338.0 1756.83  4355.3 1754.13  4378.8 1753.63  4448.8 1755.10
  4548.8 1753.20  4578.8 1754.62  4728.8 1753.72  4798.8 1752.40  4828.8 1754.25
  4898.9 1750.97  4948.9 1751.11  4958.9 1750.46  4988.9 1744.62  4996.0 1744.28
  4996.5 1743.78  5001.8 1744.28  5048.9 1750.70  5098.9 1752.44  5108.9 1751.77
  5268.9 1752.94  5298.9 1752.39  5388.9 1754.24  5508.9 1753.97  5608.9 1755.42
#Mann=3,-1,0
  4048.3    0.05       0  4996.0    0.05       0  5001.8    0.05       0
Bank Sta=4996,5001.8
Exp/Cntr=0.3,0.1