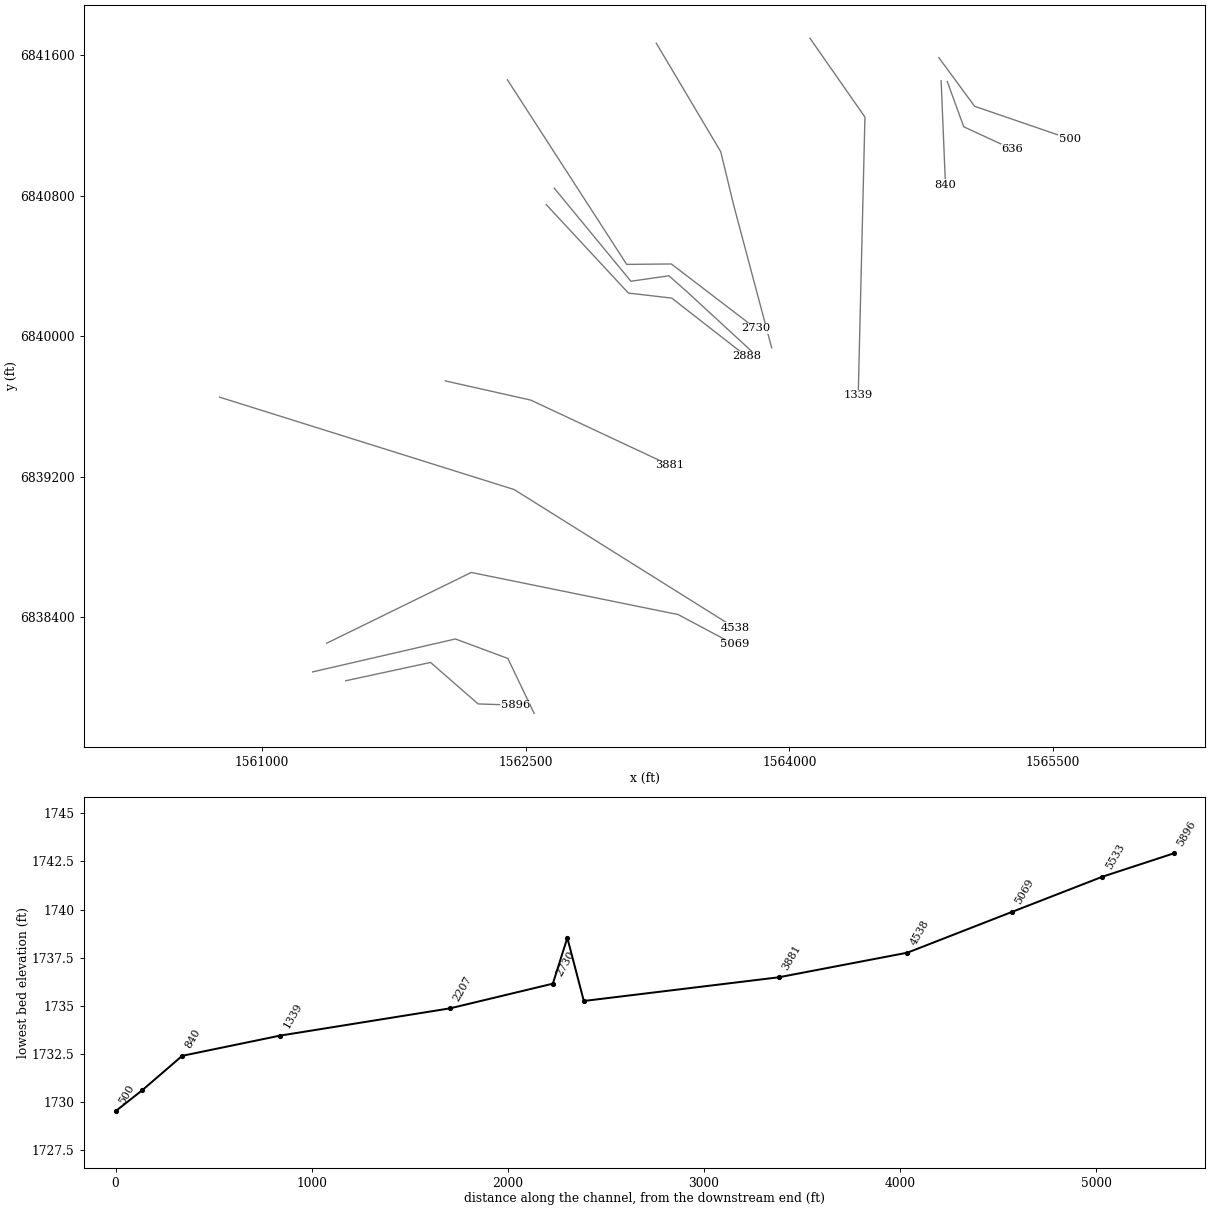
HEC-RAS study Elm 01 35.prj: Elm 01 35 Base Level Engineering

--- Elm 01 35.g01 (geometry) --- (continued)

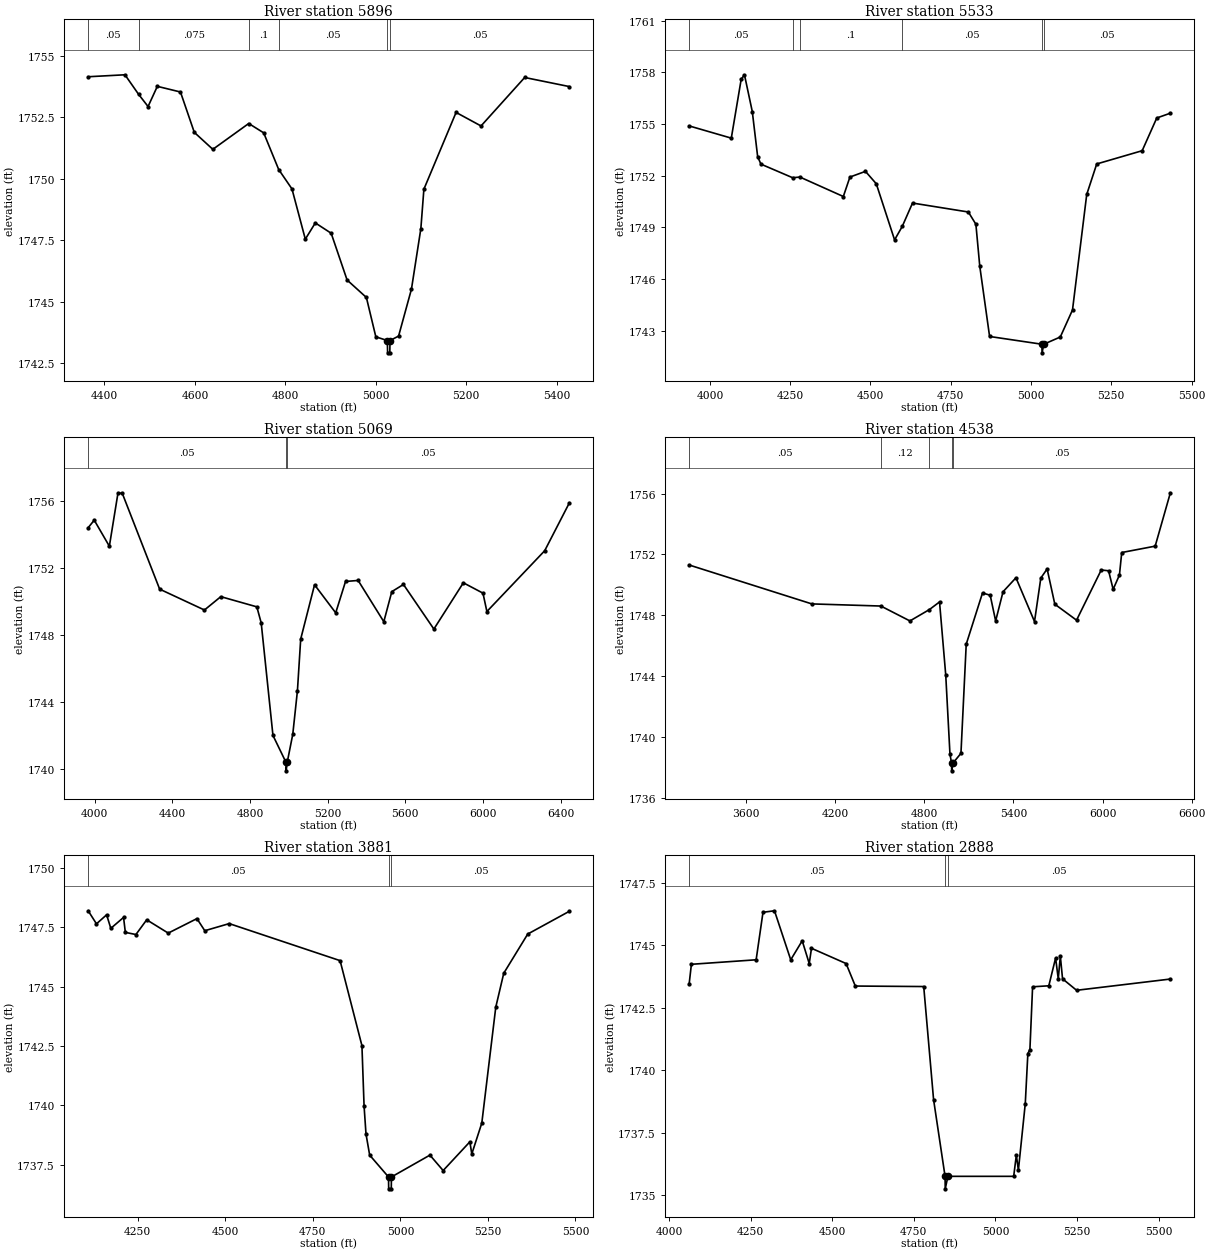
Type RM Length L Ch R = 1,5896,363,363,363
BEGIN DESCRIPTION:
Mapping XS dce648fc
END DESCRIPTION:
XS GIS Cut Line= 4
      1561475.44      6838038.69      1561958.07      6838142.85
      1562228.90      6837906.74      1562440.35      6837899.81
#Sta/Elev= 30
  4363.9 1754.14  4445.3 1754.22  4475.3 1753.43  4496.4 1752.93  4516.9 1753.75
  4568.1 1753.52  4598.7 1751.88  4639.7 1751.19  4719.1 1752.24  4752.2 1751.86
  4785.4 1750.37  4814.8 1749.58  4844.3 1747.54  4866.4 1748.20  4901.5 1747.78
  4936.7 1745.88  4979.4 1745.17  5000.3 1743.57  5025.8 1743.42  5026.3 1742.92
  5031.2 1742.92  5031.6 1743.42  5050.6 1743.60  5079.1 1745.51  5099.9 1747.97
  5106.6 1749.57  5177.8 1752.69  5233.0 1752.14  5329.6 1754.11  5428.5 1753.74
#Mann=6,-1,0
  4363.9    0.05       0  4475.3   0.075       0  4719.1     0.1       0
  4785.4    0.05       0  5025.8    0.03       0  5031.6    0.05       0
Bank Sta=5025.8,5031.6
Exp/Cntr=0.3,0.1

Type RM Length L Ch R = 1,5533,464,464,464
BEGIN DESCRIPTION:
Mapping XS d3710114
END DESCRIPTION:
XS GIS Cut Line= 4
      1561287.09      6838089.04      1562099.56      6838276.53
      1562398.18      6838165.42      1562547.45      6837852.99
#Sta/Elev= 30
  3935.3 1754.89  4066.6 1754.18  4097.4 1757.60  4107.6 1757.86  4132.0 1755.72
  4148.7 1753.10  4158.9 1752.67  4257.7 1751.88  4280.2 1751.92  4415.5 1750.79
  4436.0 1751.92  4484.4 1752.25  4518.1 1751.53  4575.1 1748.27  4598.9 1749.05
  4631.0 1750.41  4804.8 1749.89  4828.3 1749.18  4840.4 1746.74  4871.0 1742.66
  5033.9 1742.21  5034.4 1741.71  5039.7 1742.21  5091.2 1742.63  5129.2 1744.20
  5173.5 1750.91  5204.6 1752.68  5346.2 1753.45  5391.6 1755.35  5434.0 1755.63
#Mann=6,-1,0
  3935.3    0.05       0  4257.7   0.075       0  4280.2     0.1       0
  4598.9    0.05       0  5033.9    0.03       0  5039.7    0.05       0
Bank Sta=5033.9,5039.7
Exp/Cntr=0.3,0.1

Type RM Length L Ch R = 1,5069,531,531,531
BEGIN DESCRIPTION:
Mapping XS 3a8f75a2
END DESCRIPTION:
XS GIS Cut Line= 4
      1561366.88      6838252.20      1562189.84      6838655.00
      1563366.93      6838415.42      1563686.37      6838245.28
#Sta/Elev= 30
  3966.2 1754.43  3997.5 1754.88  4075.4 1753.32  4120.0 1756.52  4142.2 1756.48
  4334.5 1750.75  4565.3 1749.50  4649.6 1750.30  4835.2 1749.69  4857.7 1748.73
  4918.3 1741.99  4985.8 1740.37  4986.3 1739.87  4991.6 1740.37  5020.4 1742.06
  5044.4 1744.67  5061.2 1747.76  5132.6 1751.01  5241.6 1749.33  5292.2 1751.21
  5357.1 1751.27  5489.4 1748.80  5530.6 1750.60  5590.6 1751.03  5747.4 1748.36
  5899.2 1751.13  6000.3 1750.51  6020.5 1749.41  6318.3 1753.05  6445.6 1755.92
#Mann=3,-1,0
  3966.2    0.05       0  4985.8    0.03       0  4991.6    0.05       0
Bank Sta=4985.8,4991.6
Exp/Cntr=0.3,0.1

Type RM Length L Ch R = 1,4538,657,657,657
BEGIN DESCRIPTION:
Mapping XS 19469638
END DESCRIPTION:
XS GIS Cut Line= 3
      1560757.08      6839652.85      1562434.17      6839126.80
      1563689.38      6838340.34
#Sta/Elev= 30
  3217.8 1751.30  4043.6 1748.74  4508.2 1748.60  4703.8 1747.62  4835.3 1748.37
  4903.0 1748.87  4944.9 1744.05  4973.3 1738.85  4984.2 1738.26  4984.7 1737.76
  4992.5 1738.26  5047.2 1738.91  5082.7 1746.09  5192.3 1749.46  5244.1 1749.31
  5280.7 1747.62  5330.5 1749.54  5417.4 1750.46  5542.3 1747.58  5584.7 1750.44
  5627.2 1751.04  5679.0 1748.72  5825.2 1747.67  5991.3 1750.97  6040.9 1750.92
  6071.5 1749.70  6113.9 1750.64  6129.3 1752.12  6354.4 1752.54  6456.7 1756.05
#Mann=5,-1,0
  3217.8    0.05       0  4508.2    0.12       0  4835.3    0.05       0
  4984.2    0.03       0  4992.5    0.05       0
Bank Sta=4984.2,4992.5
Exp/Cntr=0.3,0.1

Type RM Length L Ch R = 1,3881,993,993,993
BEGIN DESCRIPTION:
Mapping XS 631c672c
END DESCRIPTION:
XS GIS Cut Line= 3
      1562041.87      6839745.27      1562528.82      6839635.91
      1563321.54      6839264.24
#Sta/Elev= 30
  4108.2 1748.19  4131.9 1747.64  4160.9 1748.02  4172.9 1747.45  4209.3 1747.91
  4214.4 1747.28  4244.6 1747.19  4275.4 1747.81  4336.9 1747.25  4418.9 1747.86
  4441.3 1747.35  4511.1 1747.65  4827.8 1746.09  4890.2 1742.51  4896.3 1739.97
  4901.8 1738.79  4912.3 1737.90  4966.1 1736.98  4966.6 1736.48  4974.0 1736.48
  4974.5 1736.98  5084.4 1737.90  5122.2 1737.25  5198.5 1738.46  5204.0 1737.95
  5232.6 1739.25  5272.5 1744.13  5295.3 1745.56  5363.8 1747.21  5482.8 1748.17
#Mann=3,-1,0
  4108.2    0.05       0  4966.1    0.03       0  4974.5    0.05       0
Bank Sta=4966.1,4974.5
Exp/Cntr=0.3,0.1

Type RM Length L Ch R = 1,2888,84,84,84
BEGIN DESCRIPTION:
Mapping XS 7c9aee82
END DESCRIPTION:
XS GIS Cut Line= 4
      1562616.13      6840748.99      1563083.92      6840245.22
      1563331.00      6840216.43      1563755.59      6839885.40
#Sta/Elev= 30
  4061.4 1743.44  4068.3 1744.23  4266.7 1744.41  4287.7 1746.31  4322.9 1746.37
  4372.7 1744.41  4407.9 1745.17  4429.4 1744.26  4436.3 1744.87  4542.3 1744.26
  4570.6 1743.36  4780.2 1743.34  4810.4 1738.82  4845.6 1735.75  4846.1 1735.25
  4854.4 1735.75  5055.9 1735.75  5064.0 1736.60  5070.3 1736.00  5091.4 1738.66
  5099.3 1740.66  5105.6 1740.82  5113.8 1743.33  5163.5 1743.37  5184.3 1744.48
  5192.5 1743.65  5198.8 1744.56  5205.6 1743.65  5248.6 1743.19  5536.0 1743.64
#Mann=3,-1,0
  4061.4    0.05       0  4845.6    0.03       0  4854.4    0.05       0
Bank Sta=4845.6,4854.4
Exp/Cntr=0.3,0.1

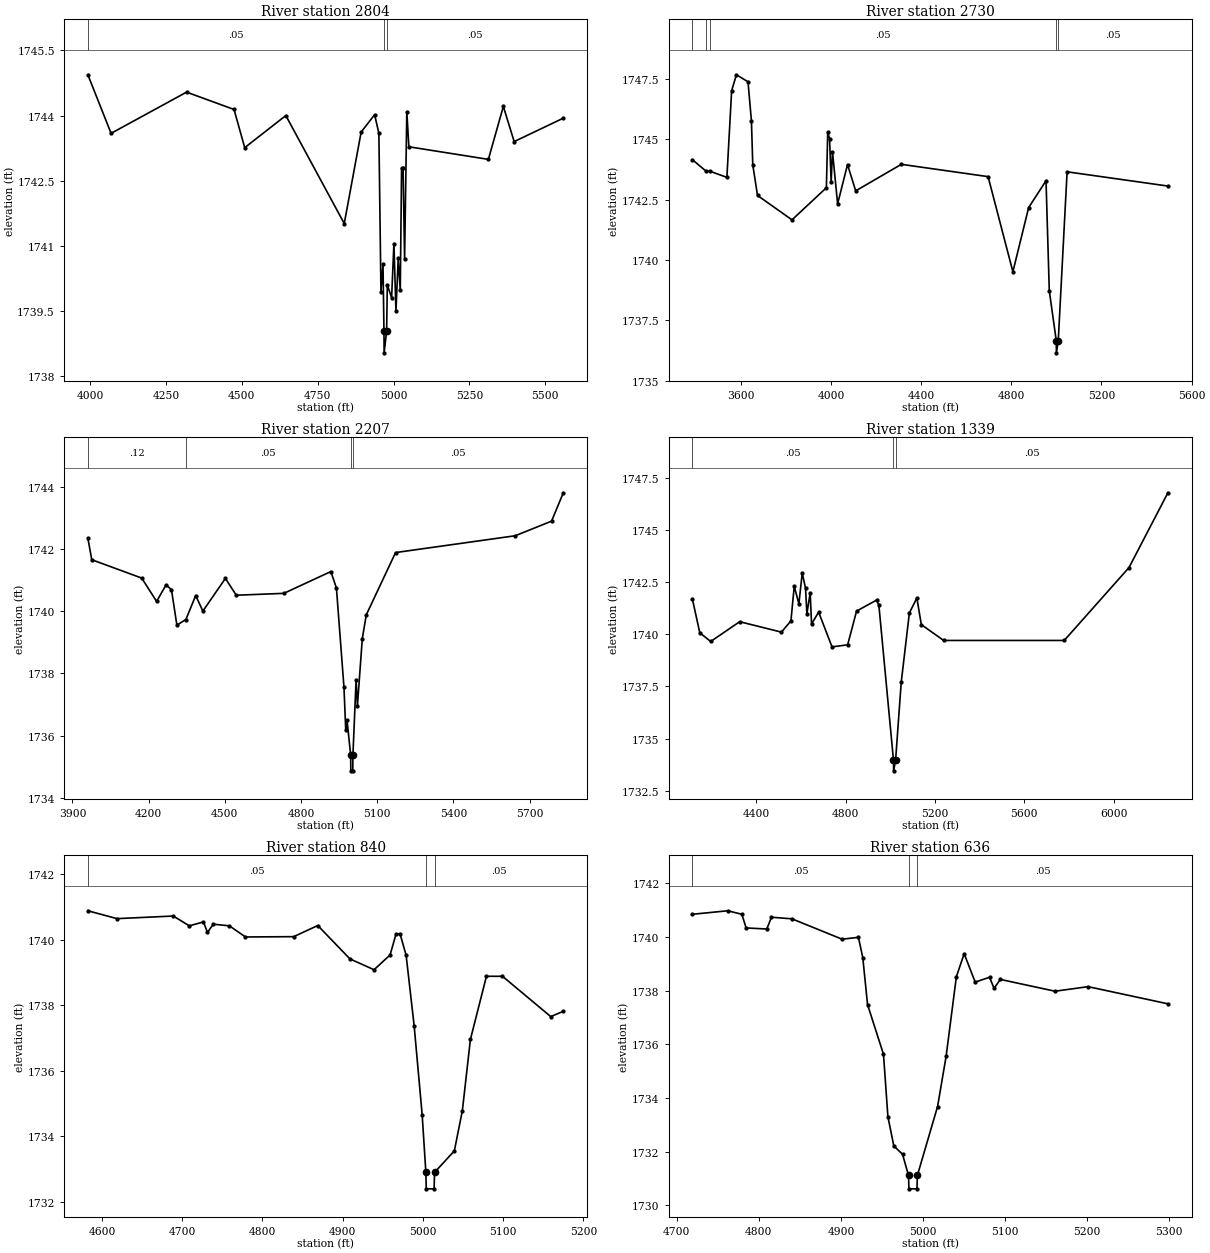
Type RM Length L Ch R = 1,2804,74,74,74
BEGIN DESCRIPTION:
Mapping XS 9a0ca8da
END DESCRIPTION:
XS GIS Cut Line= 5
      1562661.73      6840842.52      1563098.31      6840312.39
      1563314.21      6840343.57      1563412.57      6840257.21
      1563803.59      6839897.37
#Sta/Elev= 30
  3992.4 1744.94  4068.9 1743.59  4317.8 1744.54  4474.2 1744.14  4509.4 1743.26
  4644.9 1744.00  4837.5 1741.51  4893.2 1743.62  4937.6 1744.02  4951.6 1743.59
  4958.5 1739.94  4965.2 1740.58  4968.4 1739.03  4968.9 1738.53  4977.2 1739.03
  4979.4 1740.10  4993.6 1739.80  5001.2 1741.05  5007.9 1739.49  5015.4 1740.71
  5022.1 1739.97  5026.5 1742.79  5031.3 1742.79  5036.4 1740.70  5043.7 1744.09
  5050.5 1743.28  5312.6 1742.99  5361.9 1744.21  5397.6 1743.40  5559.6 1743.94
#Mann=3,-1,0
  3992.4    0.05       0  4968.4    0.05       0  4977.2    0.05       0
Bank Sta=4968.4,4977.2
Exp/Cntr=0.3,0.1

Type RM Length L Ch R = 1,2730,523,523,523
BEGIN DESCRIPTION:
Mapping XS 6bac44ed
END DESCRIPTION:
XS GIS Cut Line= 4
      1562395.55      6841458.85      1563074.32      6840408.34
      1563328.60      6840410.74      1563808.40      6840043.70
#Sta/Elev= 30
  3385.5 1744.15  3445.3 1743.68  3464.1 1743.67  3538.2 1743.42  3559.3 1747.01
  3580.5 1747.67  3631.9 1747.38  3647.1 1745.76  3653.0 1743.94  3674.1 1742.67
  3827.0 1741.66  3979.6 1742.99  3985.5 1745.30  3993.7 1745.03  4000.7 1743.23
  4006.7 1744.48  4029.4 1742.32  4073.3 1743.95  4109.6 1742.86  4312.1 1743.96
  4696.9 1743.45  4806.9 1739.51  4876.9 1742.17  4953.9 1743.28  4968.4 1738.72
  4999.4 1736.65  4999.9 1736.15  5008.2 1736.65  5047.4 1743.65  5494.6 1743.06
#Mann=5,-1,0
  3385.5    0.05       0  3445.3    0.12       0  3464.1    0.05       0
  4999.4    0.05       0  5008.2    0.05       0
Bank Sta=4999.4,5008.2
Exp/Cntr=0.3,0.1

Type RM Length L Ch R = 1,2207,868,868,868
BEGIN DESCRIPTION:
Mapping XS afe1e58e
END DESCRIPTION:
XS GIS Cut Line= 4
      1563242.77      6841667.20      1563609.59      6841049.64
      1563683.64      6840744.19      1563899.55      6839933.33
#Sta/Elev= 30
  3961.0 1742.34  3976.3 1741.65  4173.1 1741.06  4231.6 1740.31  4268.6 1740.84
  4290.0 1740.69  4311.4 1739.55  4346.9 1739.73  4385.5 1740.50  4413.7 1740.00
  4502.4 1741.05  4545.2 1740.51  4732.4 1740.57  4917.6 1741.27  4939.5 1740.74
  4969.1 1737.56  4976.2 1736.17  4981.3 1736.49  4995.6 1735.37  4996.1 1734.87
  5003.9 1734.87  5004.4 1735.37  5016.9 1737.80  5022.1 1736.96  5041.4 1739.12
  5057.0 1739.88  5172.3 1741.88  5643.5 1742.42  5786.5 1742.89  5832.7 1743.80
#Mann=4,-1,0
  3961.0    0.12       0  4346.9    0.05       0  4995.6    0.03       0
  5004.4    0.05       0
Bank Sta=4995.6,5004.4
Exp/Cntr=0.3,0.1

Type RM Length L Ch R = 1,1339,499,499,499
BEGIN DESCRIPTION:
Mapping XS 9964eb4d
END DESCRIPTION:
XS GIS Cut Line= 3
      1564117.80      6841694.93      1564430.30      6841246.93
      1564392.10      6839663.71
#Sta/Elev= 30
  4113.8 1741.68  4146.6 1740.08  4195.4 1739.66  4325.4 1740.61  4512.4 1740.11
  4554.9 1740.65  4569.7 1742.31  4590.6 1741.47  4605.5 1742.94  4620.3 1742.22
  4626.4 1740.99  4641.2 1742.00  4647.3 1740.50  4679.0 1741.07  4739.0 1739.40
  4809.0 1739.50  4849.0 1741.12  4939.0 1741.65  4949.0 1741.39  5014.4 1733.95
  5014.9 1733.45  5023.7 1733.95  5049.1 1737.71  5085.5 1741.03  5119.1 1741.75
  5139.1 1740.47  5239.1 1739.71  5779.3 1739.71  6069.4 1743.21  6243.7 1746.80
#Mann=3,-1,0
  4113.8    0.05       0  5014.4    0.03       0  5023.7    0.05       0
Bank Sta=5014.4,5023.7
Exp/Cntr=0.3,0.1

Type RM Length L Ch R = 1,840,204,204,204
BEGIN DESCRIPTION:
Mapping XS 2fae99ed
END DESCRIPTION:
XS GIS Cut Line= 2
      1564863.89      6841454.27      1564888.60      6840862.29
#Sta/Elev= 30
  4582.5 1740.89  4618.8 1740.65  4688.9 1740.73  4708.9 1740.43  4726.5 1740.55
  4731.5 1740.23  4738.9 1740.48  4758.9 1740.43  4778.9 1740.09  4839.0 1740.10
  4869.0 1740.44  4909.1 1739.42  4939.1 1739.09  4959.1 1739.54  4966.5 1740.18
  4971.5 1740.19  4979.1 1739.53  4989.1 1737.38  4999.1 1734.66  5003.7 1732.90
  5004.2 1732.40  5014.0 1732.40  5014.5 1732.90  5039.2 1733.56  5049.2 1734.79
  5059.2 1736.96  5079.2 1738.89  5099.2 1738.89  5159.3 1737.66  5175.0 1737.82
#Mann=3,-1,0
  4582.5    0.05       0  5003.7    0.03       0  5014.5    0.05       0
Bank Sta=5003.7,5014.5
Exp/Cntr=0.3,0.1

Type RM Length L Ch R = 1,636,136,136,136
BEGIN DESCRIPTION:
Mapping XS bcf12305
END DESCRIPTION:
XS GIS Cut Line= 3
      1564899.04      6841448.41      1564992.79      6841191.46
      1565270.24      6841063.14
#Sta/Elev= 30
  4719.1 1740.85  4762.1 1740.98  4779.2 1740.85  4784.5 1740.34  4809.7 1740.30
  4815.3 1740.74  4840.3 1740.68  4901.4 1739.92  4921.3 1739.99  4926.6 1739.23
  4932.4 1737.48  4951.8 1735.63  4957.2 1733.30  4964.4 1732.21  4975.0 1731.90
  4982.3 1731.11  4982.8 1730.61  4992.6 1730.61  4993.1 1731.11  5017.7 1733.68
  5028.1 1735.55  5040.6 1738.52  5050.1 1739.38  5063.5 1738.32  5081.0 1738.50
  5086.5 1738.09  5094.2 1738.42  5160.8 1737.98  5201.1 1738.15  5298.3 1737.51
#Mann=3,-1,0
  4719.1    0.05       0  4982.3    0.03       0  4993.1    0.05       0
Bank Sta=4982.3,4993.1
Exp/Cntr=0.3,0.1

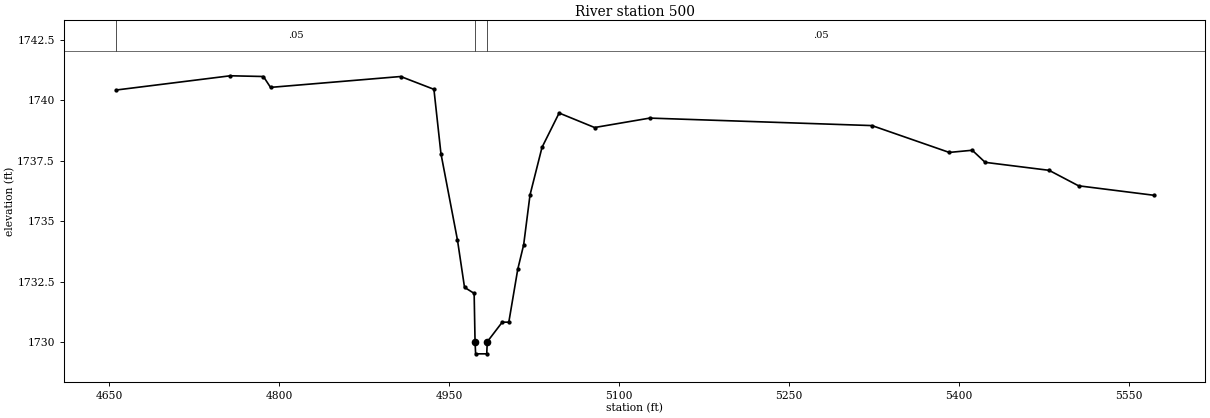
Type RM Length L Ch R = 1,500,0,0,0
BEGIN DESCRIPTION:
Elm 01 35 1.0
END DESCRIPTION:
XS GIS Cut Line= 3
      1564850.86      6841585.10      1565054.66      6841308.09
      1565595.51      6841122.52
#Sta/Elev= 30
  4656.1 1740.43  4757.0 1741.02  4786.2 1740.99  4792.5 1740.54  4907.4 1740.99
  4936.7 1740.46  4942.9 1737.80  4957.5 1734.22  4963.7 1732.27  4972.2 1732.02
  4973.0 1730.02  4973.5 1729.52  4983.3 1729.52  4983.8 1730.02  4997.0 1730.83
  5002.8 1730.83  5010.7 1733.02  5015.9 1734.03  5021.5 1736.09  5032.1 1738.06
  5047.2 1739.48  5078.5 1738.88  5127.2 1739.27  5323.3 1738.96  5391.5 1737.85
  5411.8 1737.94  5423.2 1737.44  5479.6 1737.11  5505.6 1736.47  5571.8 1736.08
#Mann=3,-1,0
  4656.1    0.05       0  4973.0    0.03       0  4983.8    0.05       0
Bank Sta=4973,4983.8
Exp/Cntr=0.3,0.1

Chan Stop Cuts=-1