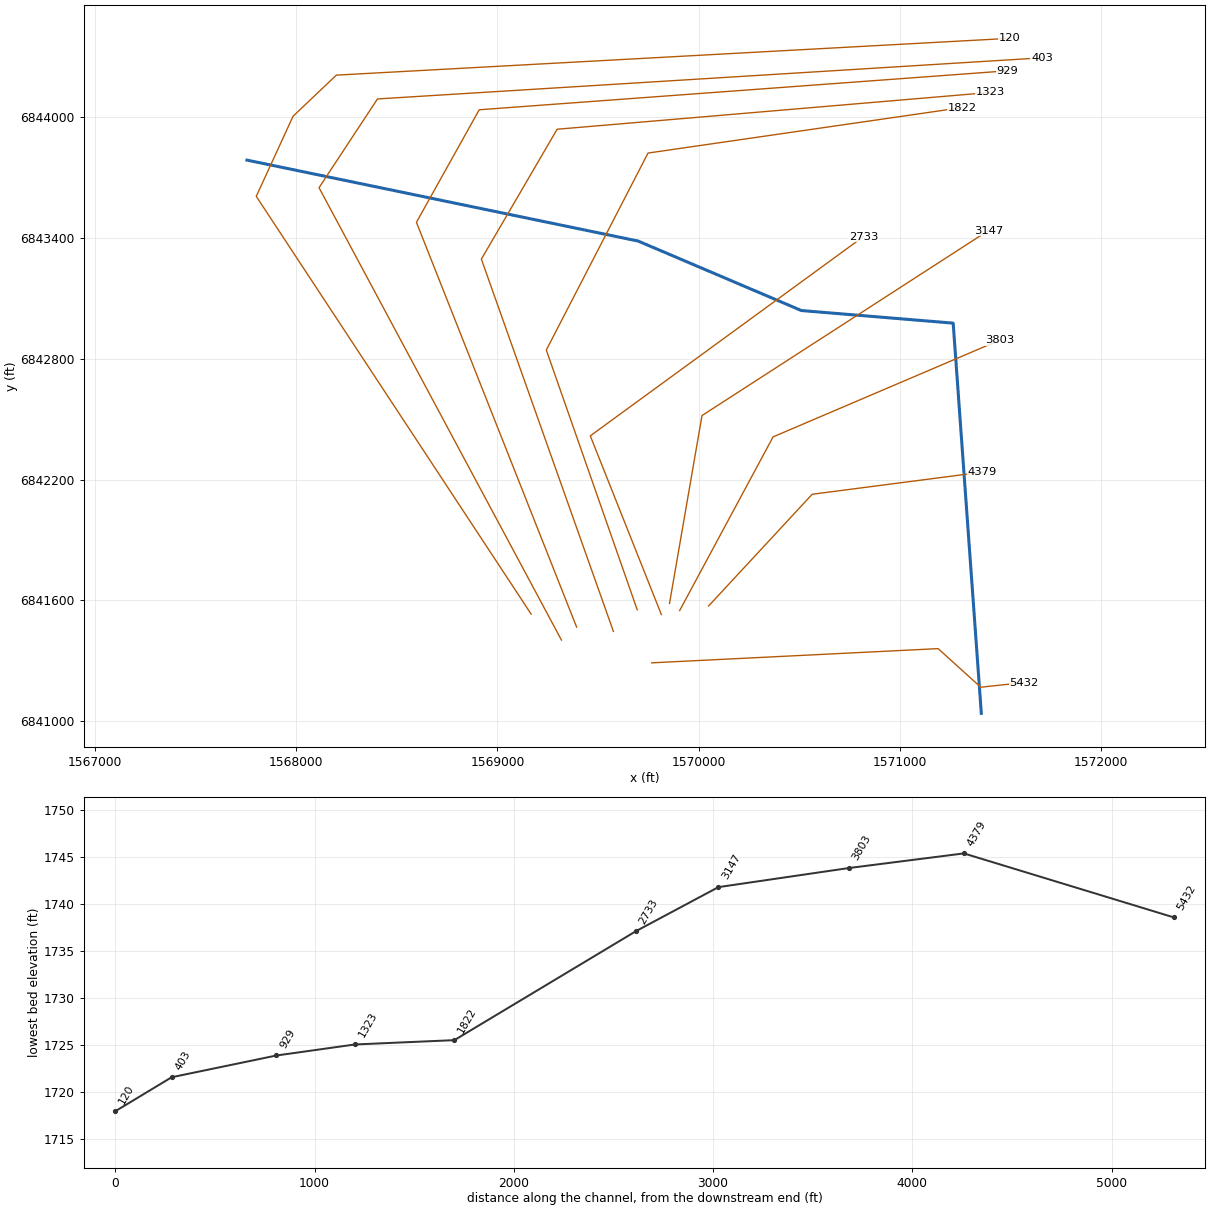
--- Elm 01 37.prj (project) ---

Proj Title=Elm 01 37 Base Level Engineering
Current Plan=p01
Default Exp/Contr=0.3,0.1
English Units
Geom File=g01
Flow File=f01
Plan File=p01
BEGIN DESCRIPTION:
Elm 01 37
END DESCRIPTION:

--- Elm 01 37.p01 (plan) ---

Plan Title=Multiple Run
Short Identifier=Multiple
Geom File=g01
Flow File=f01
Subcritical Flow
K Sum by GR= 0
Std Step Tol= 0.01
Critical Tol= 0.01
Num of Std Step Trials= 20
Max Error Tol= 0.3
Flow Tol Ratio= 0.001
Split Flow NTrial= 30
Split Flow Tol= 0.02
Split Flow Ratio= 0.02
Log Output Level= 0
Friction Slope Method= 1
Unsteady Friction Slope Method= 2
Unsteady Bridges Friction Slope Method= 1
Parabolic Critical Depth
Global Vel Dist=  1 , 1 , 1
Global Log Level= 0
CheckData=True
Encroach Param= -1, 0, 0, 0
BEGIN DESCRIPTION:
Multiple Run
END DESCRIPTION:

--- Elm 01 37.f01 (steady flow) ---

Flow Title=Multiple
Number of Profiles=7
Profile Names=10-year,25-year,50-year,1pct_min,100-year,1pct_plu,500-year
River Rch & RM= Elm 01 37,Reach-1,5432
     150     199     237     175     280     386     398
River Rch & RM= Elm 01 37,Reach-1,3147
     174     233     279     208     333     458     479
Boundary for River Rch & Prof#=Elm 01 37,Reach-1,1
Up Type=0
Dn Type=3
Dn Slope=0.005
Boundary for River Rch & Prof#=Elm 01 37,Reach-1,2
Up Type=0
Dn Type=3
Dn Slope=0.005
Boundary for River Rch & Prof#=Elm 01 37,Reach-1,3
Up Type=0
Dn Type=3
Dn Slope=0.005
Boundary for River Rch & Prof#=Elm 01 37,Reach-1,4
Up Type=0
Dn Type=3
Dn Slope=0.005
Boundary for River Rch & Prof#=Elm 01 37,Reach-1,5
Up Type=0
Dn Type=3
Dn Slope=0.005
Boundary for River Rch & Prof#=Elm 01 37,Reach-1,6
Up Type=0
Dn Type=3
Dn Slope=0.005
Boundary for River Rch & Prof#=Elm 01 37,Reach-1,7
Up Type=0
Dn Type=3
Dn Slope=0.005

--- Elm 01 37.g01 (geometry) ---

Geom Title=Existing Conditions

River Reach=Elm 01 37,Reach-1
Reach XY= 5
      1571405.00      6841038.00      1571265.18      6842977.68
      1570510.94      6843040.26      1569699.47      6843385.61
      1567755.00      6843788.00

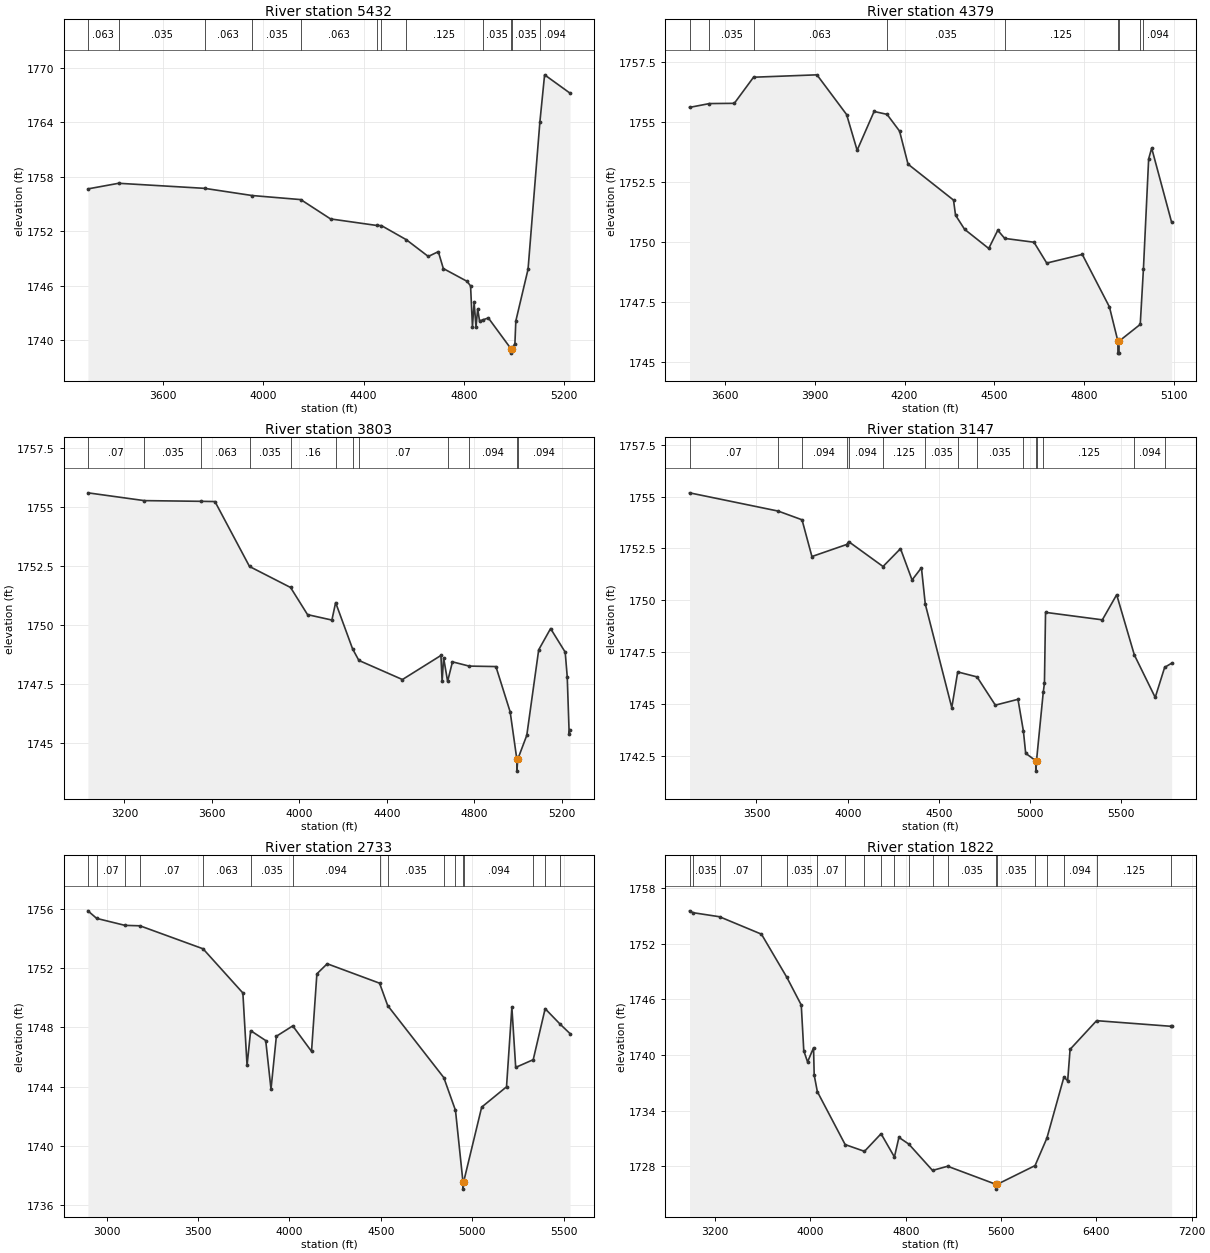
Type RM Length L Ch R = 1,5432,1053,1053,1053
BEGIN DESCRIPTION:
Elm Overflow 10.0
END DESCRIPTION:
XS GIS Cut Line= 4
      1569766.90      6841289.18      1571190.35      6841359.85
      1571402.35      6841168.04      1571615.92      6841191.00
#Sta/Elev= 30
  3298.6 1756.67  3421.4 1757.29  3765.2 1756.73  3954.5 1755.94  4149.1 1755.49
  4267.9 1753.36  4452.1 1752.64  4471.4 1752.62  4570.4 1751.07  4658.4 1749.22
  4698.4 1749.75  4718.4 1747.89  4813.1 1746.48  4827.3 1745.97  4834.8 1741.49
  4841.5 1744.15  4849.0 1741.46  4855.7 1743.44  4863.2 1742.10  4875.4 1742.22
  4898.3 1742.44  4988.2 1739.06  4988.5 1738.56  4992.2 1739.06  5004.4 1739.59
  5008.1 1742.11  5056.9 1747.81  5104.2 1764.06  5123.0 1769.25  5224.5 1767.23
#Mann=12,-1,0
  3298.6   0.063       0  3421.4   0.035       0  3765.2   0.063       0
  3954.5   0.035       0  4149.1   0.063       0  4452.1   0.035       0
  4471.4   0.094       0  4570.4   0.125       0  4875.4   0.035       0
  4988.2   0.035       0  4992.2   0.035       0  5104.2   0.094       0
Bank Sta=4988.2,4992.2
Exp/Cntr=0.3,0.1

Type RM Length L Ch R = 1,4379,576,576,576
BEGIN DESCRIPTION:
Elm Overflow 9.0
END DESCRIPTION:
XS GIS Cut Line= 3
      1570049.54      6841571.84      1570564.42      6842127.11
      1571411.15      6842237.13
#Sta/Elev= 30
  3481.4 1755.61  3548.0 1755.77  3631.1 1755.78  3695.3 1756.87  3907.2 1756.97
  4006.4 1755.31  4041.5 1753.82  4098.2 1755.44  4141.4 1755.32  4183.3 1754.62
  4211.6 1753.24  4363.6 1751.74  4370.3 1751.11  4400.6 1750.52  4481.3 1749.72
  4511.5 1750.48  4534.7 1750.14  4632.5 1749.98  4675.1 1749.11  4793.9 1749.47
  4884.6 1747.28  4912.9 1745.85  4913.1 1745.35  4916.6 1745.35  4916.9 1745.85
  4987.6 1746.55  4998.3 1748.88  5015.7 1753.46  5025.8 1753.91  5092.5 1750.81
#Mann=9,-1,0
  3481.4    0.07       0  3548.0   0.035       0  3695.3   0.063       0
  4141.4   0.035       0  4534.7   0.125       0  4912.9   0.094       0
  4916.9   0.125       0  4987.6   0.063       0  4998.3   0.094       0
Bank Sta=4912.9,4916.9
Exp/Cntr=0.3,0.1

Type RM Length L Ch R = 1,3803,656,656,656
BEGIN DESCRIPTION:
Elm Overflow 8.0
END DESCRIPTION:
XS GIS Cut Line= 3
      1569905.70      6841549.16      1570370.08      6842412.31
      1571496.72      6842893.16
#Sta/Elev= 30
  3032.7 1755.59  3290.6 1755.26  3552.3 1755.23  3613.9 1755.22  3771.9 1752.47
  3959.7 1751.58  4037.3 1750.43  4148.7 1750.20  4165.8 1750.94  4243.3 1748.98
  4272.1 1748.49  4471.3 1747.68  4647.4 1748.70  4652.9 1747.60  4659.7 1748.60
  4678.0 1747.60  4700.1 1748.43  4776.2 1748.25  4898.9 1748.23  4964.1 1746.31
  4994.7 1744.30  4995.0 1743.80  4998.7 1744.30  5040.2 1745.32  5094.6 1748.94
  5149.0 1749.84  5215.8 1748.84  5225.1 1747.80  5234.0 1745.38  5237.8 1745.55
#Mann=12,-1,0
  3032.7    0.07       0  3290.6   0.035       0  3552.3   0.063       0
  3771.9   0.035       0  3959.7    0.16       0  4165.8    0.07       0
  4243.3    0.16       0  4272.1    0.07       0  4678.0   0.125       0
  4776.2   0.094       0  4994.7   0.094       0  4998.7   0.094       0
Bank Sta=4994.7,4998.7
Exp/Cntr=0.3,0.1

Type RM Length L Ch R = 1,3147,414,414,414
BEGIN DESCRIPTION:
Elm Overflow 7.0
END DESCRIPTION:
XS GIS Cut Line= 3
      1569855.21      6841584.49      1570016.74      6842518.31
      1571440.61      6843438.08
#Sta/Elev= 30
  3132.9 1755.18  3619.1 1754.30  3749.6 1753.88  3803.8 1752.11  3994.1 1752.69
  4005.1 1752.83  4193.7 1751.63  4289.4 1752.49  4352.8 1750.98  4404.2 1751.57
  4425.2 1749.82  4570.5 1744.83  4603.0 1746.55  4708.9 1746.31  4809.3 1744.95
  4933.4 1745.23  4963.1 1743.70  4975.6 1742.63  5031.0 1742.27  5031.3 1741.77
  5035.0 1742.27  5071.8 1745.56  5078.5 1746.01  5084.5 1749.42  5395.9 1749.06
  5474.4 1750.27  5571.2 1747.37  5685.7 1745.32  5737.4 1746.77  5775.7 1746.97
#Mann=15,-1,0
  3132.9    0.07       0  3619.1   0.035       0  3749.6   0.094       0
  3994.1   0.125       0  4005.1   0.094       0  4193.7   0.125       0
  4425.2   0.035       0  4603.0   0.063       0  4708.9   0.035       0
  4963.1   0.094       0  5031.0   0.094       0  5035.0   0.094       0
  5071.8   0.125       0  5571.2   0.094       0  5737.4   0.125       0
Bank Sta=5031,5035
Exp/Cntr=0.3,0.1

Type RM Length L Ch R = 1,2733,911,911,911
BEGIN DESCRIPTION:
Elm Overflow 6.0
END DESCRIPTION:
XS GIS Cut Line= 3
      1569814.82      6841528.97      1569461.49      6842417.36
      1570819.79      6843408.25
#Sta/Elev= 30
  2897.8 1755.86  2945.8 1755.35  3100.4 1754.88  3182.6 1754.85  3527.7 1753.30
  3745.6 1750.32  3768.5 1745.43  3788.1 1747.78  3870.6 1747.11  3899.5 1743.83
  3928.8 1747.40  4018.6 1748.10  4121.2 1746.38  4150.5 1751.61  4206.9 1752.29
  4493.4 1750.98  4537.8 1749.47  4844.9 1744.61  4908.7 1742.40  4949.5 1737.59
  4949.8 1737.09  4953.5 1737.59  5052.0 1742.62  5187.9 1743.99  5217.2 1749.35
  5238.1 1745.30  5334.0 1745.82  5399.2 1749.26  5480.0 1748.23  5535.2 1747.58
#Mann=16,-1,0
  2897.8   0.035       0  2945.8    0.07       0  3100.4   0.035       0
  3182.6    0.07       0  3527.7   0.063       0  3788.1   0.035       0
  4018.6   0.094       0  4493.4   0.063       0  4537.8   0.035       0
  4844.9   0.063       0  4908.7   0.094       0  4949.5   0.094       0
  4953.5   0.094       0  5334.0   0.063       0  5399.2   0.094       0
  5480.0   0.125       0
Bank Sta=4949.5,4953.5
Exp/Cntr=0.3,0.1

Type RM Length L Ch R = 1,1822,499,499,499
BEGIN DESCRIPTION:
Elm Overflow 5.0
END DESCRIPTION:
XS GIS Cut Line= 4
      1569694.71      6841552.91      1569242.82      6842844.01
      1569748.49      6843823.07      1571308.49      6844049.00
#Sta/Elev= 30
  2985.3 1755.57  3014.8 1755.37  3237.5 1754.93  3588.9 1753.05  3802.4 1748.38
  3923.0 1745.40  3944.2 1740.46  3976.0 1739.25  4026.2 1740.79  4031.5 1737.84
  4058.2 1736.04  4291.5 1730.33  4453.6 1729.60  4592.8 1731.50  4704.8 1728.99
  4742.6 1731.11  4825.9 1730.38  5024.6 1727.54  5151.7 1727.99  5560.7 1726.02
  5560.9 1725.52  5564.8 1726.02  5885.2 1728.06  5984.8 1731.04  6127.7 1737.63
  6158.9 1737.21  6179.1 1740.61  6401.7 1743.71  7028.5 1743.10  7031.4 1743.10
#Mann=20,-1,0
  2985.3    0.07       0  3014.8   0.035       0  3237.5    0.07       0
  3588.9   0.063       0  3802.4   0.035       0  4058.2    0.07       0
  4291.5   0.035       0  4453.6   0.035       0  4592.8   0.063       0
  4704.8   0.063       0  4825.9   0.035       0  5024.6   0.035       0
  5151.7   0.035       0  5560.7   0.063       0  5564.8   0.035       0
  5885.2   0.094       0  5984.8   0.125       0  6127.7   0.094       0
  6401.7   0.125       0  7028.5   0.094       0
Bank Sta=5560.7,5564.8
Exp/Cntr=0.3,0.1

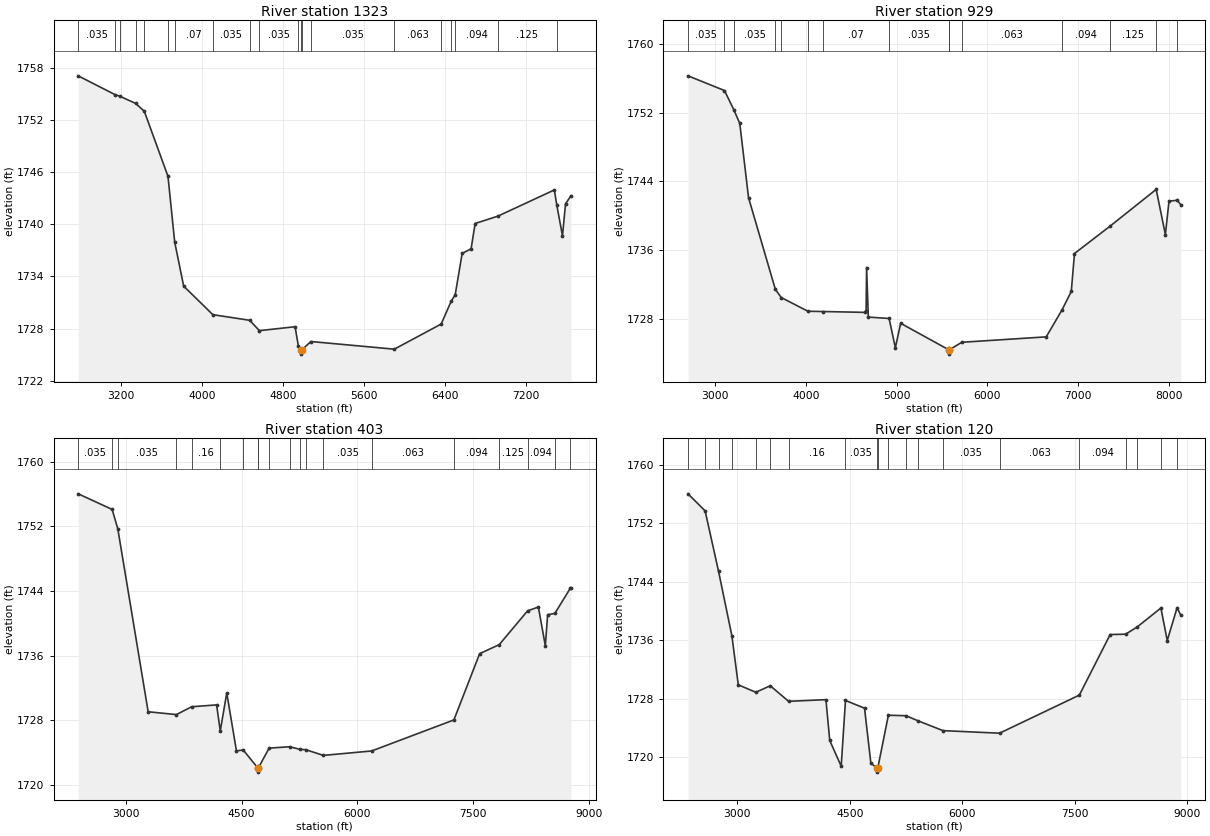
Type RM Length L Ch R = 1,1323,394,394,394
BEGIN DESCRIPTION:
Elm Overflow 4.0
END DESCRIPTION:
XS GIS Cut Line= 4
      1569576.36      6841445.32      1568920.06      6843295.88
      1569296.62      6843941.41      1571448.43      6844124.32
#Sta/Elev= 30
  2777.2 1757.06  3139.4 1754.91  3185.7 1754.73  3345.2 1753.89  3430.8 1752.98
  3664.6 1745.51  3731.4 1737.93  3819.8 1732.88  4107.7 1729.60  4472.1 1728.95
  4568.3 1727.76  4920.9 1728.21  4953.5 1725.99  4984.2 1725.56  4984.4 1725.06
  4988.4 1725.56  5077.0 1726.51  5901.3 1725.63  6365.0 1728.52  6464.1 1731.15
  6503.4 1731.88  6572.4 1736.64  6660.6 1737.17  6700.8 1740.08  6925.9 1740.93
  7483.6 1743.94  7507.6 1742.20  7563.9 1738.66  7594.0 1742.34  7647.6 1743.27
#Mann=20,-1,0
  2777.2   0.035       0  3139.4    0.07       0  3185.7   0.035       0
  3345.2    0.07       0  3430.8   0.063       0  3664.6   0.035       0
  3731.4    0.07       0  4107.7   0.035       0  4472.1    0.07       0
  4568.3   0.035       0  4953.5   0.094       0  4984.2   0.094       0
  4988.4   0.094       0  5077.0   0.035       0  5901.3   0.063       0
  6365.0   0.094       0  6464.1   0.125       0  6503.4   0.094       0
  6925.9   0.125       0  7507.6   0.094       0
Bank Sta=4984.2,4988.4
Exp/Cntr=0.3,0.1

Type RM Length L Ch R = 1,929,526,526,526
BEGIN DESCRIPTION:
Elm Overflow 3.0
END DESCRIPTION:
XS GIS Cut Line= 4
      1569393.44      6841466.88      1568597.29      6843478.78
      1568909.30      6844038.24      1571534.48      6844231.90
#Sta/Elev= 30
  2697.8 1756.28  3099.9 1754.57  3202.4 1752.35  3269.0 1750.74  3365.8 1742.09
  3661.5 1731.43  3725.7 1730.48  4021.2 1728.88  4182.4 1728.85  4645.6 1728.75
  4662.8 1728.94  4668.2 1733.97  4687.1 1728.20  4916.5 1728.04  4985.5 1724.63
  5043.8 1727.48  5575.9 1724.39  5576.1 1723.89  5580.1 1724.39  5718.9 1725.27
  6650.0 1725.90  6824.5 1729.04  6926.3 1731.18  6961.7 1735.60  7358.6 1738.82
  7863.1 1743.06  7964.5 1737.81  8004.6 1741.69  8095.2 1741.80  8134.4 1741.28
#Mann=15,-1,0
  2697.8   0.035       0  3099.9   0.063       0  3202.4   0.035       0
  3661.5    0.07       0  3725.7   0.035       0  4021.2    0.16       0
  4182.4    0.07       0  4916.5   0.035       0  5575.9   0.035       0
  5580.1   0.035       0  5718.9   0.063       0  6824.5   0.094       0
  7358.6   0.125       0  7863.1   0.094       0  8095.2   0.125       0
Bank Sta=5575.9,5580.1
Exp/Cntr=0.3,0.1

Type RM Length L Ch R = 1,403,283,283,283
BEGIN DESCRIPTION:
Elm Overflow 2.0
END DESCRIPTION:
XS GIS Cut Line= 4
      1569318.15      6841402.29      1568113.14      6843650.92
      1568403.63      6844092.04      1571706.59      6844296.45
#Sta/Elev= 30
  2382.5 1756.02  2823.0 1754.09  2896.6 1751.67  3289.9 1729.05  3656.6 1728.70
  3853.1 1729.67  4177.0 1729.90  4224.6 1726.67  4308.6 1731.38  4434.5 1724.21
  4521.3 1724.33  4712.7 1722.08  4712.9 1721.58  4716.9 1722.08  4858.1 1724.55
  5123.4 1724.72  5259.2 1724.40  5335.7 1724.35  5561.6 1723.65  6187.7 1724.20
  7253.6 1728.04  7587.3 1736.24  7841.6 1737.36  8209.1 1741.54  8348.7 1742.01
  8438.9 1737.22  8468.9 1741.06  8562.5 1741.22  8761.1 1744.31  8771.1 1744.34
#Mann=20,-1,0
  2382.5   0.035       0  2823.0   0.063       0  2896.6   0.035       0
  3656.6   0.035       0  3853.1    0.16       0  4224.6    0.07       0
  4521.3    0.07       0  4712.7   0.035       0  4716.9    0.07       0
  4858.1   0.035       0  5123.4    0.07       0  5259.2    0.07       0
  5335.7    0.16       0  5561.6   0.035       0  6187.7   0.063       0
  7253.6   0.094       0  7841.6   0.125       0  8209.1   0.094       0
  8562.5   0.125       0  8761.1   0.063       0
Bank Sta=4712.7,4716.9
Exp/Cntr=0.3,0.1

Type RM Length L Ch R = 1,120,0,0,0
BEGIN DESCRIPTION:
Elm Overflow 1.0
END DESCRIPTION:
XS GIS Cut Line= 5
      1569167.51      6841531.43      1567801.13      6843607.89
      1567984.03      6844005.97      1568199.21      6844210.38
      1571545.24      6844393.29
#Sta/Elev= 30
  2342.9 1756.06  2571.0 1753.73  2750.4 1745.45  2927.9 1736.64  3013.3 1729.92
  3247.2 1728.90  3440.1 1729.79  3684.3 1727.66  4182.3 1727.89  4233.2 1722.30
  4385.8 1718.78  4443.0 1727.78  4697.0 1726.72  4781.5 1719.20  4868.4 1718.47
  4868.7 1717.97  4872.7 1718.47  5015.2 1725.76  5250.6 1725.69  5411.5 1724.99
  5743.2 1723.65  6497.8 1723.30  7561.6 1728.51  7972.9 1736.80  8179.2 1736.85
  8332.1 1737.83  8649.5 1740.43  8734.0 1735.98  8865.2 1740.47  8914.5 1739.46
#Mann=20,-1,0
  2342.9   0.035       0  2571.0   0.063       0  2750.4   0.063       0
  2927.9   0.035       0  3247.2   0.035       0  3440.1    0.16       0
  3684.3    0.16       0  4443.0   0.035       0  4868.4   0.063       0
  4872.7   0.035       0  5015.2   0.035       0  5250.6   0.035       0
  5411.5    0.16       0  5743.2   0.035       0  6497.8   0.063       0
  7561.6   0.094       0  8179.2   0.125       0  8332.1   0.094       0
  8649.5   0.094       0  8865.2   0.125       0
Bank Sta=4868.4,4872.7
Exp/Cntr=0.3,0.1

Chan Stop Cuts=-1