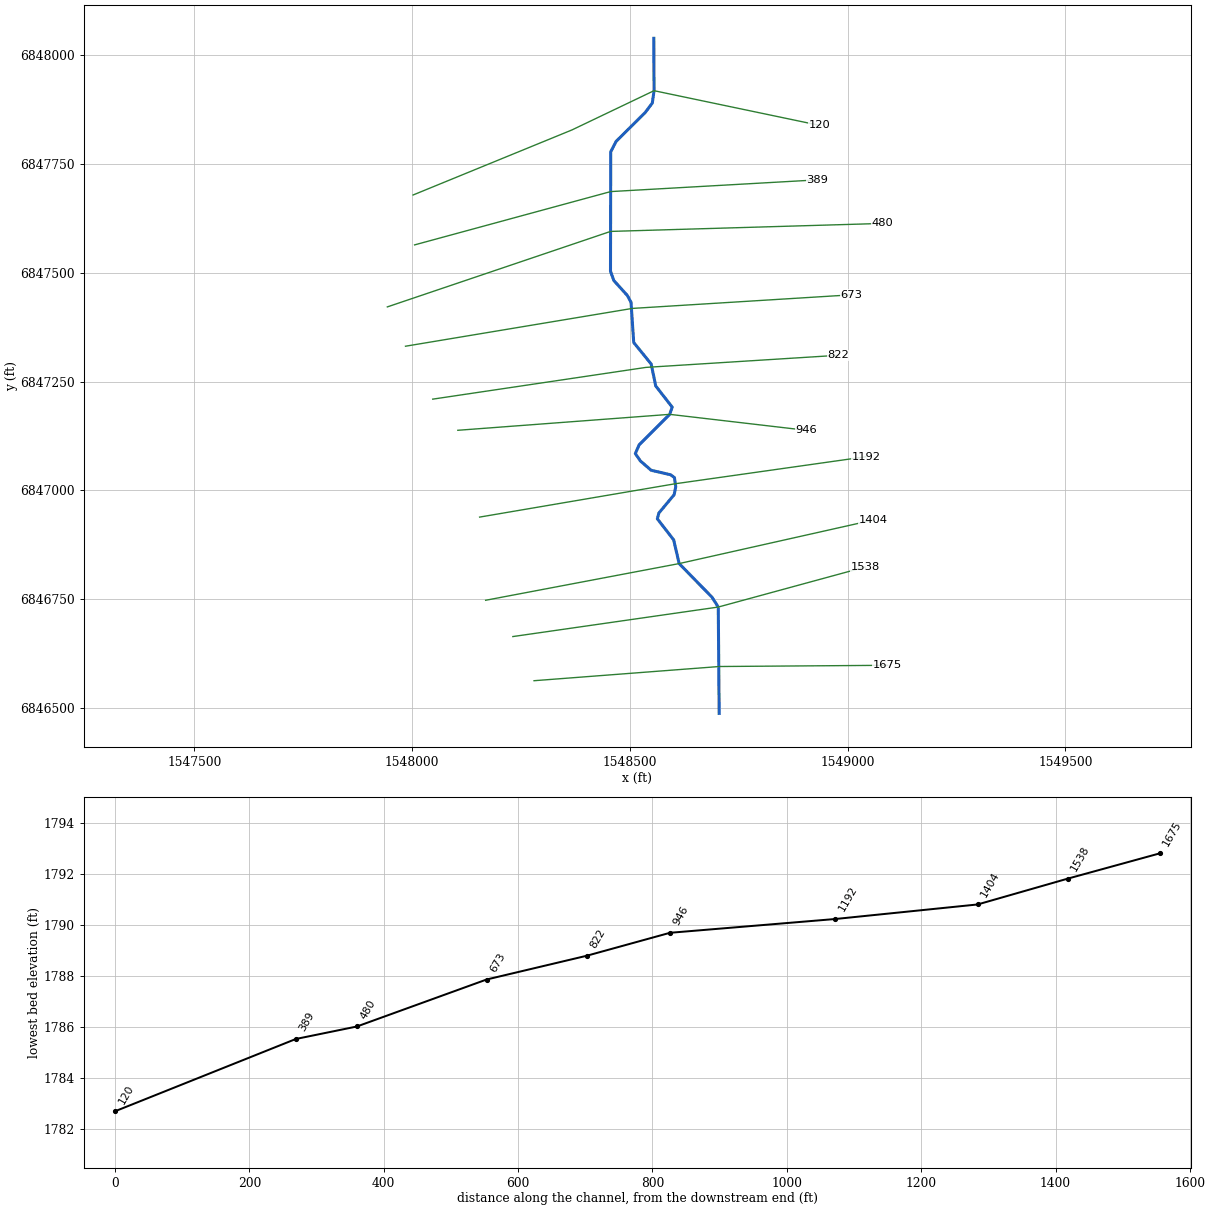
--- Elm 01 40.prj (project) ---

Proj Title=Elm 01 40 Base Level Engineering
Current Plan=p01
Default Exp/Contr=0.3,0.1
English Units
Geom File=g01
Flow File=f01
Plan File=p01
Y Axis Title=Elevation
X Axis Title(PF)=Main Channel Distance
X Axis Title(XS)=Station
BEGIN DESCRIPTION:
Elm 01 40
END DESCRIPTION:
DSS Export Rating Curves= 0
DSS Export Rating Curve Sorted= 0
DSS Export Volume Flow Curves= 0
DXF OffsetX= 0
DXF OffsetY= 0
DXF ScaleX= 1
DXF ScaleY= 10

--- Elm 01 40.p01 (plan) ---

Plan Title=Multiple Run
Program Version=4.10
Short Identifier=Multiple
Geom File=g01
Flow File=f01
Subcritical Flow
K Sum by GR= 0
Std Step Tol= 0.01
Critical Tol= 0.01
Num of Std Step Trials= 20
Max Error Tol= 0.3
Flow Tol Ratio= 0.001
Split Flow NTrial= 30
Split Flow Tol= 0.02
Split Flow Ratio= 0.02
Log Output Level= 0
Friction Slope Method= 1
Unsteady Friction Slope Method= 2
Unsteady Bridges Friction Slope Method= 1
Parabolic Critical Depth
Global Vel Dist= 1 , 1 , 1
Global Log Level= 0
CheckData=True
Encroach Param=-1 ,0,0, 0
BEGIN DESCRIPTION:
Multiple Run
END DESCRIPTION:
Computation Interval=1HOUR
Output Interval=1HOUR
Run HTab= 0
Run UNet= 0
Run PostProcess= 0
Run WQNet= 0
UNET Theta= 1
UNET Theta Warmup= 1
UNET ZTol= 0.02
UNET ZSATol= 0.05
UNET MxIter= 20
UNET MaxInSteps= 0
UNET DtIC= 0
UNET DtMin= 0
UNET MaxCRTS= 20
UNET WFStab= 2
UNET SFStab= 1
UNET WFX= 1
UNET SFX= 1
UNET DSS MLevel= 4
UNET DZMax Abort= 100
UNET Convert EG Bridges= 0
UNET Use Existing IB Tables=-1
UNET Froude Reduction=False
UNET Froude Limit= 1
UNET Froude Power= 10
UNET Time Slicing=0,0, 5
UNET Junction Losses=0
Instantaneous Interval=1HOUR
Write IC File= 0
Write IC File at Sim End=0
Echo Input=False
Echo Parameters=False
Echo Output=False
Write Detailed= 0
WQ AD Non Conservative
WQ ULTIMATE=-1
WQ Max Comp Step=1HOUR
WQ Output Interval=15MIN
WQ Output Selected Increments= 0
WQ Output face flow=0
WQ Output face velocity=0
WQ Output face area=0
WQ Output face dispersion=0
WQ Output cell volume=0
WQ Output cell surface area=0
WQ Output cell continuity=0
WQ Output cumulative cell continuity=0
WQ Output face conc=0
WQ Output face dconc_dx=0
WQ Output face courant=0
WQ Output face peclet=0
WQ Output face adv mass=0
WQ Output face disp mass=0
WQ Output cell mass=0
WQ Output cell source sink temp=0
WQ Output cell source sink nsm=0
WQ Output MaxMinRange=-1
WQ Daily Max Min Mean=-1
WQ Daily Range=0
WQ Daily Time=0
WQ Create Restart=0
WQ Fixed Restart=0
WQ System Summary=0
WQ Use Fixed Temperature=0
Sorting and Armoring Iterations= 10
XS Update Threshold= 0.02
Hydraulics Update Threshold= 0.02
Energy Slope Method= 1
Volume Change Method= 0
XS Weighting Method= 0
Number of US Weighted Cross Sections= 1
Number of DS Weighted Cross Sections= 1
Upstream XS Weight=0.25
Main XS Weight=0.5
Downstream XS Weight=0.25
Number of DS XS's Weighted with US Boundary= 1
Upstream Boundary Weight= 1
Weight of XSs Associated with US Boundary= 0
Number of US XS's Weighted with DS Boundary= 1
Downstream Boundary Weight= 0.5
Weight of XSs Associated with DS Boundary= 0.5
Sediment Output Level= 4
Mass or Volume Output= 0
Output Increment Type= 1
Profile and TS Output Increment= 10
XS Output Flag= 0
XS Output Increment= 10
Disregard all LS=0
Disregard all Conn=0
Disregard all Breaches=0
Disregard all Pumps=0

--- Elm 01 40.f01 (steady flow) ---

Flow Title=Multiple
Number of Profiles=7
Profile Names=10-year,25-year,50-year,1pct_min,100-year,1pct_plu,500-year
River Rch & RM= Elm 01 40,Reach-1,1675
      33      40      45      32      51      70      65
Boundary for River Rch & Prof#=Elm 01 40,Reach-1,1
Up Type=0
Dn Type=3
Dn Slope=0.005
Boundary for River Rch & Prof#=Elm 01 40,Reach-1,2
Up Type=0
Dn Type=3
Dn Slope=0.005
Boundary for River Rch & Prof#=Elm 01 40,Reach-1,3
Up Type=0
Dn Type=3
Dn Slope=0.005
Boundary for River Rch & Prof#=Elm 01 40,Reach-1,4
Up Type=0
Dn Type=3
Dn Slope=0.005
Boundary for River Rch & Prof#=Elm 01 40,Reach-1,5
Up Type=0
Dn Type=3
Dn Slope=0.005
Boundary for River Rch & Prof#=Elm 01 40,Reach-1,6
Up Type=0
Dn Type=3
Dn Slope=0.005
Boundary for River Rch & Prof#=Elm 01 40,Reach-1,7
Up Type=0
Dn Type=3
Dn Slope=0.005

--- Elm 01 40.g01 (geometry) ---

Geom Title=Existing Conditions
Program Version=4.10

River Reach=Elm 01 40       ,Reach-1
Reach XY= 30
        1548705.        6846488.      1548702.94      6846732.15
      1548688.54      6846754.75      1548613.14      6846831.96
      1548600.55      6846886.35      1548563.08      6846934.72
      1548566.54      6846947.98      1548601.57      6846990.01
      1548605.34      6847008.42      1548602.28       6847029.5
      1548593.52      6847035.88      1548548.69      6847046.28
      1548524.17      6847067.66      1548512.55      6847084.43
      1548521.24      6847104.58      1548591.43      6847174.62
      1548597.15      6847191.23      1548559.43      6847239.63
      1548548.91      6847290.17      1548508.83      6847339.58
      1548502.64      6847432.02      1548494.11      6847447.63
      1548463.14      6847481.94      1548455.52      6847503.22
      1548456.06      6847777.56       1548468.4      6847801.31
      1548535.35      6847867.85      1548551.49      6847889.45
      1548555.51      6847917.79        1548555.        6848038.

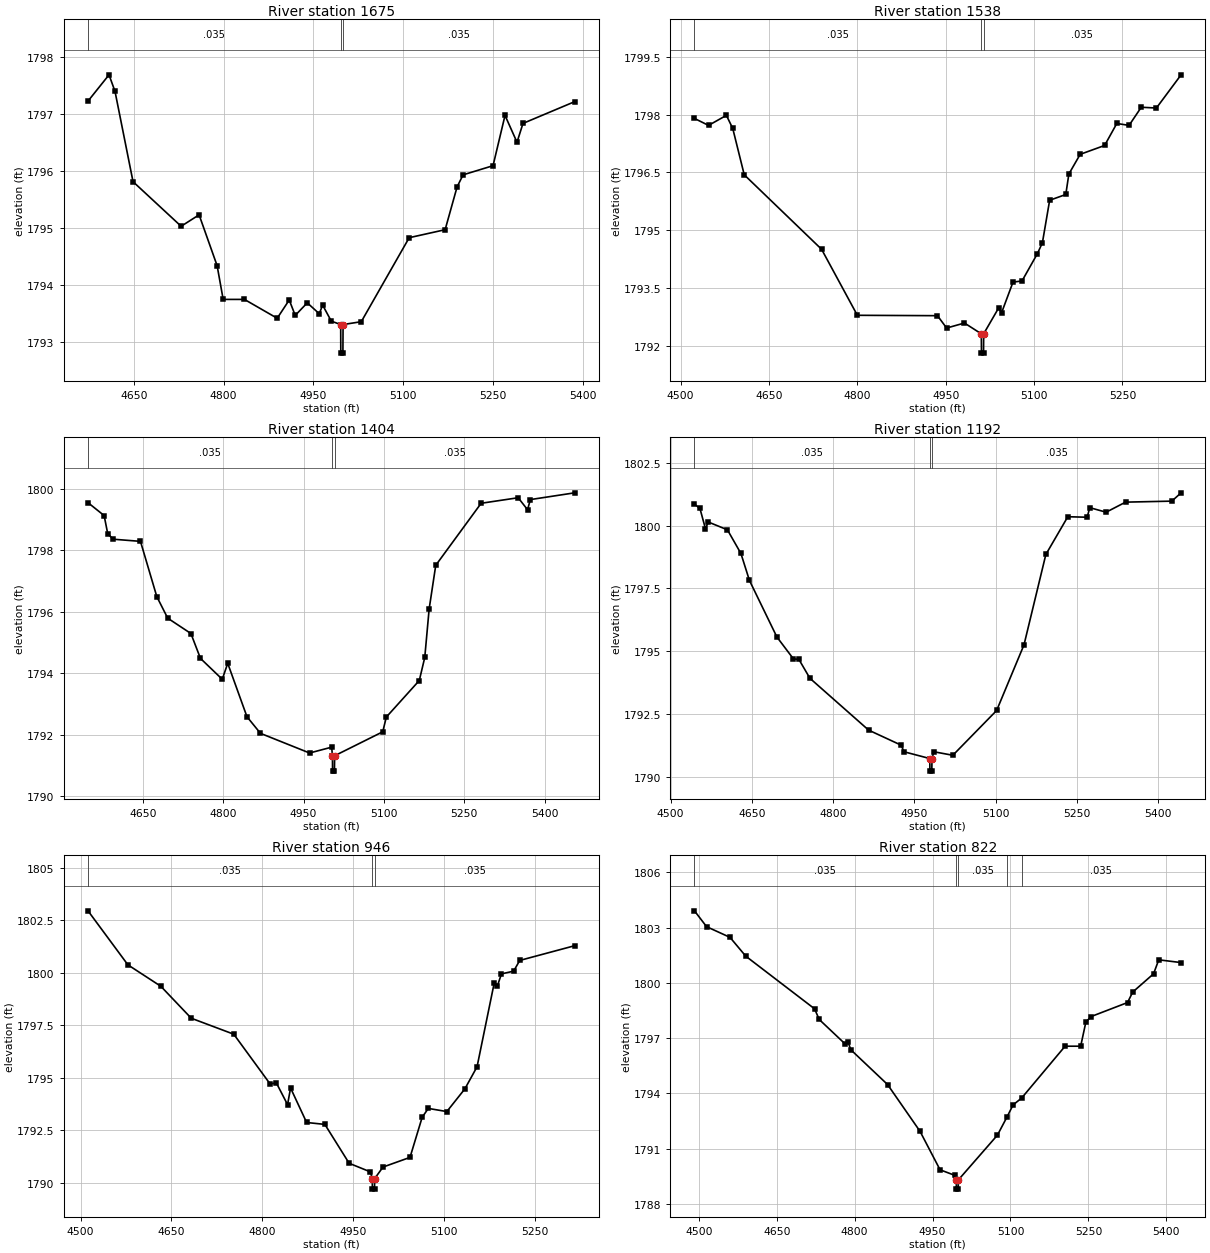
Type RM Length L Ch R = 1 ,1675    ,137,137,137
BEGIN DESCRIPTION:
Elm 01 40 1675.015
END DESCRIPTION:
XS GIS Cut Line= 3
      1548279.99        6846563.      1548705.25       6846595.6
      1549091.24       6846598.4
#Sta/Elev= 30
  4573.5 1797.22  4608.6 1797.68  4618.6 1797.39  4648.7 1795.81    4729 1795.03
    4759 1795.23  4789.1 1794.34  4799.2 1793.75  4834.7 1793.75  4889.4 1793.42
  4909.5 1793.74  4919.5 1793.47  4939.6 1793.69  4959.6  1793.5  4965.3 1793.65
  4979.7 1793.37  4995.4 1793.31  4995.6 1792.81  4999.1 1792.81  4999.4 1793.31
  5029.8 1793.36  5109.8 1794.83  5169.8 1794.97  5189.8 1795.72  5199.8 1795.93
  5249.8 1796.09  5269.8 1796.97  5289.8  1796.5  5299.8 1796.83    5386 1797.21
#Mann= 3 ,-1 , 0
  4573.5    .035       0  4995.4    .035       0  4999.4    .035       0
Bank Sta=4995.4,4999.4
XS Rating Curve= 0 ,0
Exp/Cntr=0.3,0.1

Type RM Length L Ch R = 1 ,1538    ,134,134,134
BEGIN DESCRIPTION:
Elm 01 40 1538.359
END DESCRIPTION:
XS GIS Cut Line= 3
      1548231.38      6846664.38      1548702.94      6846732.15
      1549040.24      6846824.05
#Sta/Elev= 30
  4523.6  1797.9  4547.5 1797.72  4577.8 1797.98  4588.6 1797.64  4608.1 1796.44
  4739.4 1794.51  4800.1  1792.8  4936.1 1792.79  4951.6 1792.47  4981.9  1792.6
  5010.5 1792.32  5010.8 1791.82  5014.3 1791.82  5014.5 1792.32  5039.9 1792.99
    5045 1792.87  5064.3 1793.66  5079.6 1793.69  5105.8  1794.4  5114.2 1794.68
  5126.5 1795.78  5153.9 1795.93  5159.1 1796.46  5178.3 1796.97  5219.8  1797.2
  5240.5 1797.77  5261.3 1797.72    5282 1798.19  5307.7 1798.17  5349.6 1799.03
#Mann= 3 ,-1 , 0
  4523.6    .035       0  5010.5    .035       0  5014.5    .035       0
Bank Sta=5010.5,5014.5
XS Rating Curve= 0 ,0
Exp/Cntr=0.3,0.1

Type RM Length L Ch R = 1 ,1404    ,212,212,212
BEGIN DESCRIPTION:
Elm 01 40 1403.639
END DESCRIPTION:
XS GIS Cut Line= 3
      1548168.86       6846747.7      1548613.14      6846831.96
      1549057.78      6846931.74
#Sta/Elev= 30
  4547.8 1799.55  4577.9 1799.13  4584.6 1798.54  4594.8 1798.36  4645.7 1798.29
  4676.2 1796.49  4696.5 1795.79  4739.8 1795.29  4757.6 1794.48  4798.3  1793.8
  4808.5 1794.32  4844.4 1792.58  4869.6 1792.04  4961.2  1791.4  5002.4 1791.59
  5003.9 1791.31  5004.1 1790.81  5007.6 1790.81  5007.9 1791.31  5097.7 1792.09
  5104.4 1792.57  5165.9 1793.76  5176.1 1794.51  5184.3 1796.09  5196.6 1797.51
  5281.3 1799.53  5350.4 1799.71  5367.9 1799.32  5373.1 1799.65  5455.7 1799.87
#Mann= 3 ,-1 , 0
  4547.8    .035       0  5003.9    .035       0  5007.9    .035       0
Bank Sta=5003.9,5007.9
XS Rating Curve= 0 ,0
Exp/Cntr=0.3,0.1

Type RM Length L Ch R = 1 ,1192    ,246,246,246
BEGIN DESCRIPTION:
Elm 01 40 1192.1
END DESCRIPTION:
XS GIS Cut Line= 3
      1548155.03      6846938.69      1548602.93      6847015.07
      1549041.97       6847077.3
#Sta/Elev= 30
  4544.2 1800.85  4554.3 1800.68  4564.5 1799.87  4569.7 1800.14    4605 1799.83
  4629.9 1798.89  4645.6 1797.82  4696.3 1795.57  4726.8  1794.7  4736.9 1794.68
  4757.2 1793.93  4865.5 1791.87  4925.7 1791.27  4930.7 1791.01  4978.4 1790.74
  4978.6 1790.24  4982.1 1790.24  4982.4 1790.74  4985.8 1791.01  5020.9 1790.87
  5101.7 1792.65  5152.2 1795.26  5192.5 1798.85    5233 1800.35  5268.6 1800.33
  5273.6 1800.71  5303.7 1800.53  5339.6 1800.93  5424.9 1800.97    5442  1801.3
#Mann= 3 ,-1 , 0
  4544.2    .035       0  4978.4    .035       0  4982.4    .035       0
Bank Sta=4978.4,4982.4
XS Rating Curve= 0 ,0
Exp/Cntr=0.3,0.1

Type RM Length L Ch R = 1 ,946     ,124,124,124
BEGIN DESCRIPTION:
Elm 01 40 945.813
END DESCRIPTION:
XS GIS Cut Line= 3
        1548105.        6847138.      1548591.43      6847174.62
      1548904.99        6847138.
#Sta/Elev= 30
  4512.2 1802.94  4578.1 1800.37  4632.5 1799.35  4682.7 1797.83  4752.9 1797.07
    4813  1794.7  4823.1 1794.76  4841.7 1793.72  4846.7 1794.51  4873.2 1792.87
  4903.3 1792.78  4943.4 1790.93  4978.5 1790.52  4981.5  1790.2  4981.8  1789.7
  4985.3  1789.7  4985.5  1790.2  4999.3 1790.75  5043.9 1791.21    5064 1793.12
  5074.1 1793.54  5104.7 1793.39  5134.5 1794.47  5154.6 1795.52  5183.1 1799.53
  5188.1 1799.36  5194.9 1799.94    5215 1800.07  5225.1 1800.58  5315.7 1801.28
#Mann= 3 ,-1 , 0
  4512.2    .035       0  4981.5    .035       0  4985.5    .035       0
Bank Sta=4981.5,4985.5
XS Rating Curve= 0 ,0
Exp/Cntr=0.3,0.1

Type RM Length L Ch R = 1 ,822     ,149,149,149
BEGIN DESCRIPTION:
Elm 01 40 821.71
END DESCRIPTION:
XS GIS Cut Line= 3
      1548047.37      6847209.52      1548536.96      6847282.43
       1548977.9      6847310.21
#Sta/Elev= 30
  4491.6 1803.91  4514.9 1803.05    4560 1802.47  4590.3 1801.45  4722.8 1798.59
  4731.8 1798.01  4782.1 1796.67  4787.1 1796.81  4792.5 1796.37  4863.3 1794.48
  4925.8 1791.94  4964.4 1789.85  4992.6 1789.55  4995.6  1789.3  4995.9  1788.8
  4999.4  1788.8  4999.6  1789.3  5074.8 1791.73  5093.7 1792.74  5104.9 1793.37
  5121.6 1793.75  5205.1 1796.56  5235.1 1796.56  5245.1 1797.87  5255.2 1798.17
  5325.3 1798.93  5335.3  1799.5  5375.4 1800.49  5385.4 1801.25  5428.4  1801.1
#Mann= 5 ,-1 , 0
  4491.6    .035       0  4995.6    .035       0  4999.6    .035       0
  5093.7     .07       0  5121.6    .035       0
Bank Sta=4995.6,4999.6
XS Rating Curve= 0 ,0
Exp/Cntr=0.3,0.1

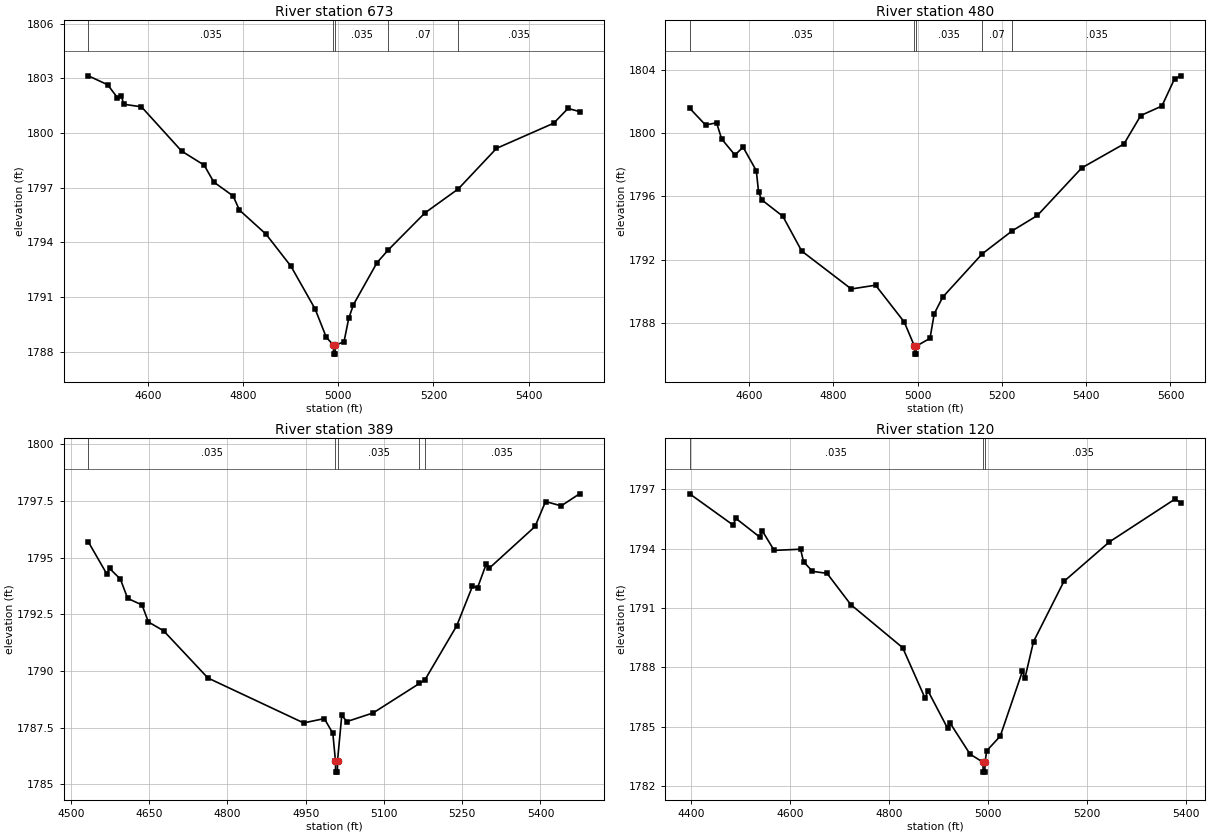
Type RM Length L Ch R = 1 ,673     ,193,193,193
BEGIN DESCRIPTION:
Elm 01 40 672.82
END DESCRIPTION:
XS GIS Cut Line= 3
       1547984.9      6847331.05      1548505.71      6847417.85
      1549009.15       6847449.1
#Sta/Elev= 30
  4474.6 1803.14  4515.2 1802.65  4535.5 1801.95  4543.9 1802.04    4549 1801.58
  4586.2 1801.44  4670.7 1799.01    4718 1798.24  4738.3 1797.31  4778.8 1796.55
  4792.3 1795.77  4848.1 1794.45  4900.5 1792.69  4951.2 1790.35  4974.8 1788.79
  4989.7 1788.37    4990 1787.87  4993.5 1787.87  4993.7 1788.37  5011.9 1788.54
  5021.9 1789.83  5031.9 1790.59  5081.4 1792.89  5104.7 1793.58  5182.2 1795.62
  5252.4 1796.94  5332.5 1799.16  5452.7 1800.54  5482.8 1801.35    5507 1801.18
#Mann= 5 ,-1 , 0
  4474.6    .035       0  4989.7    .035       0  4993.7    .035       0
  5104.7     .07       0  5252.4    .035       0
Bank Sta=4989.7,4993.7
XS Rating Curve= 0 ,0
Exp/Cntr=0.3,0.1

Type RM Length L Ch R = 1 ,480     ,91,91,91
BEGIN DESCRIPTION:
Elm 01 40 480.157
END DESCRIPTION:
XS GIS Cut Line= 3
      1547943.22      6847421.33       1548455.7      6847594.66
      1549080.03        6847613.
#Sta/Elev= 30
    4459 1801.58  4496.6 1800.52  4522.8 1800.66  4534.8 1799.64  4566.4 1798.62
  4585.7 1799.12  4617.1 1797.63  4622.4  1796.3  4629.8 1795.79    4680 1794.75
  4724.8 1792.55  4842.5 1790.15  4900.1 1790.39  4968.2 1788.06  4992.4 1786.53
  4992.6 1786.03  4996.1 1786.03  4996.4 1786.53  5029.3 1787.03  5039.3 1788.58
  5059.3 1789.63  5153.1 1792.37  5224.5 1793.83  5284.2  1794.8  5389.5 1797.81
  5489.5 1799.32  5529.5 1801.12  5579.6 1801.72  5609.6 1803.44  5624.6 1803.63
#Mann= 5 ,-1 , 0
    4459    .035       0  4992.4    .035       0  4996.4    .035       0
  5153.1     .07       0  5224.5    .035       0
Bank Sta=4992.4,4996.4
XS Rating Curve= 0 ,0
Exp/Cntr=0.3,0.1

Type RM Length L Ch R = 1 ,389     ,269,269,269
BEGIN DESCRIPTION:
Elm 01 40 388.708
END DESCRIPTION:
XS GIS Cut Line= 3
      1548005.73      6847563.69      1548455.88      6847686.11
      1548930.02        6847713.
#Sta/Elev= 30
  4533.5 1795.69    4569 1794.27  4574.2 1794.52  4594.9 1794.05  4608.8  1793.2
  4636.4 1792.91  4648.6 1792.16  4677.8 1791.77  4762.7 1789.69  4946.1 1787.71
  4985.8  1787.9  5002.1 1787.25  5007.1 1786.04  5007.4 1785.54  5010.9 1785.54
  5011.1 1786.04  5019.2 1788.04  5029.2 1787.77  5079.3 1788.15  5168.1 1789.45
  5178.4  1789.6  5239.5 1791.99  5269.6 1793.73  5279.6 1793.68  5296.4 1794.73
  5301.4 1794.52  5389.7 1796.37  5409.8 1797.47  5439.8 1797.28  5474.9 1797.81
#Mann= 5 ,-1 , 0
  4533.5    .035       0  5007.1    .035       0  5011.1    .035       0
  5168.1     .07       0  5178.4    .035       0
Bank Sta=5007.1,5011.1
XS Rating Curve= 0 ,0
Exp/Cntr=0.3,0.1

Type RM Length L Ch R = 1 ,120     ,0,0,0
BEGIN DESCRIPTION:
Elm 01 40 120.214
END DESCRIPTION:
XS GIS Cut Line= 4
      1548002.26      6847678.28      1548366.82      6847827.57
      1548555.51      6847917.79      1548936.24      6847837.99
#Sta/Elev= 30
  4396.9 1796.78  4484.7  1795.2  4490.1 1795.54  4538.1  1794.6  4543.5 1794.91
  4567.5 1793.92  4620.9 1793.98  4626.8 1793.35  4644.9 1792.86  4674.3 1792.76
  4722.3 1791.18  4827.1    1789  4872.5 1786.44    4878 1786.83  4917.8 1784.93
  4923.4 1785.17  4963.2 1783.62  4989.4 1783.21  4989.6 1782.71  4993.1 1782.71
  4993.4 1783.21  4996.9 1783.79  5024.2 1784.53    5069 1787.81  5074.1 1787.47
  5091.4 1789.31  5152.7 1792.35  5244.7 1794.35  5377.5 1796.52    5389 1796.32
#Mann= 3 ,-1 , 0
  4396.9    .035       0  4989.4    .035       0  4993.4    .035       0
Bank Sta=4989.4,4993.4
XS Rating Curve= 0 ,0
Exp/Cntr=0.3,0.1

Chan Stop Cuts=-1
Use User Specified Reach Order=0
Composite Channel Slope=5