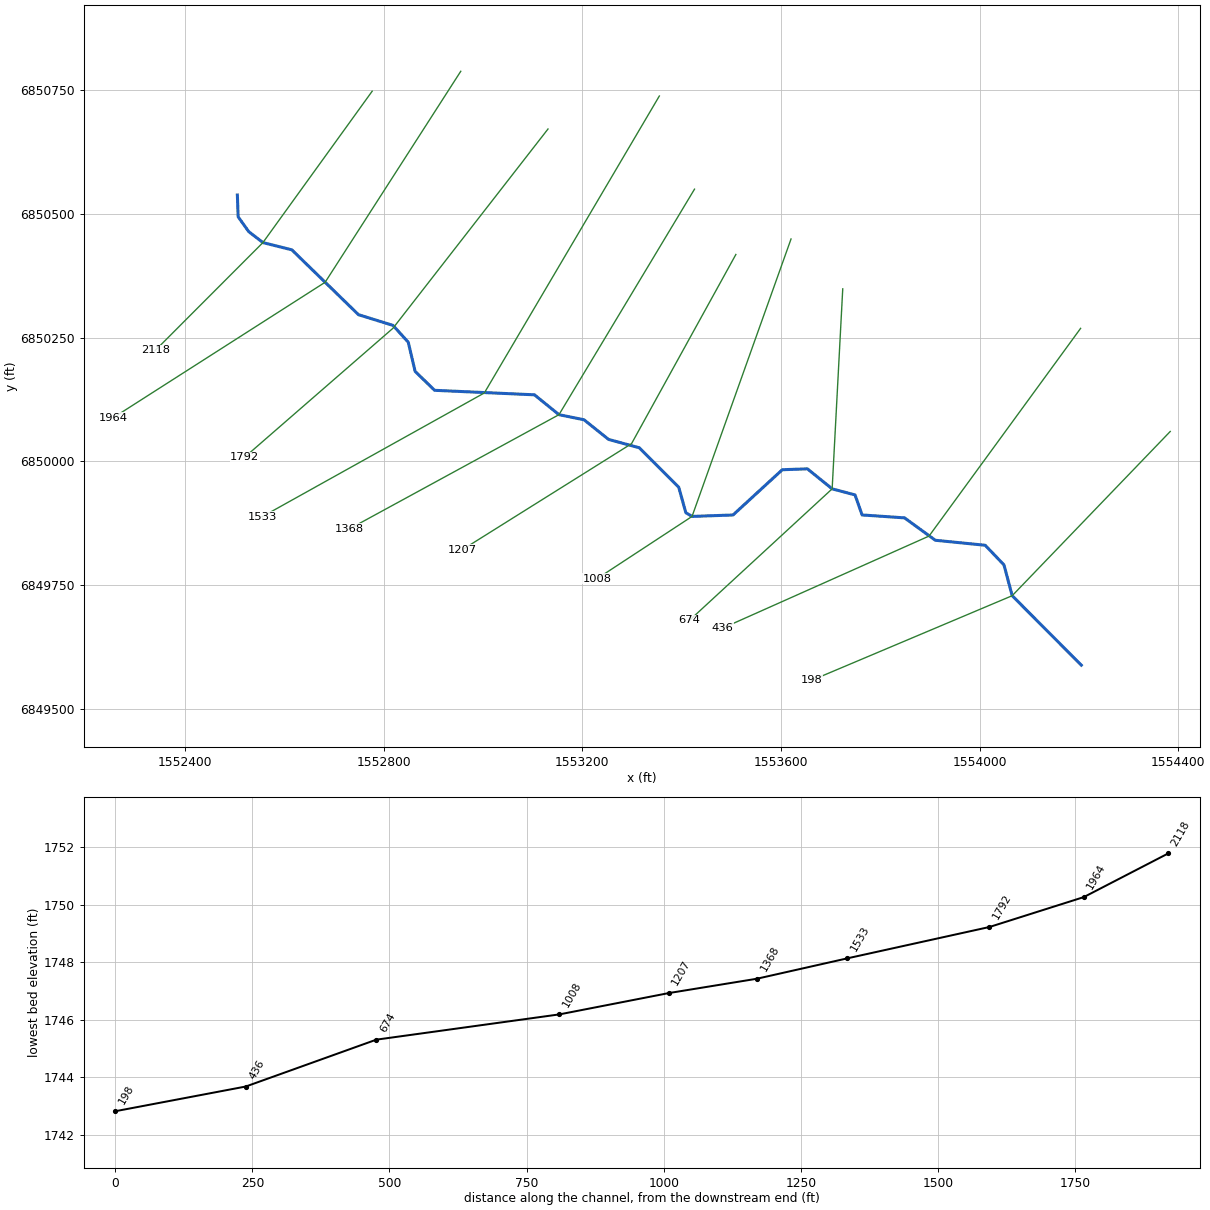
--- Elm 01 41.prj (project) ---

Proj Title=Elm 01 41 Base Level Engineering
Current Plan=p01
Default Exp/Contr=0.3,0.1
English Units
Geom File=g01
Flow File=f01
Plan File=p01
BEGIN DESCRIPTION:
Elm 01 41
END DESCRIPTION:

--- Elm 01 41.p01 (plan) ---

Plan Title=Multiple Run
Short Identifier=Multiple
Geom File=g01
Flow File=f01
Subcritical Flow
K Sum by GR= 0
Std Step Tol= 0.01
Critical Tol= 0.01
Num of Std Step Trials= 20
Max Error Tol= 0.3
Flow Tol Ratio= 0.001
Split Flow NTrial= 30
Split Flow Tol= 0.02
Split Flow Ratio= 0.02
Log Output Level= 0
Friction Slope Method= 1
Unsteady Friction Slope Method= 2
Unsteady Bridges Friction Slope Method= 1
Parabolic Critical Depth
Global Vel Dist=  1 , 1 , 1
Global Log Level= 0
CheckData=True
Encroach Param= -1, 0, 0, 0
BEGIN DESCRIPTION:
Multiple Run
END DESCRIPTION:

--- Elm 01 41.f01 (steady flow) ---

Flow Title=Multiple
Number of Profiles=7
Profile Names=10-year,25-year,50-year,1pct_min,100-year,1pct_plu,500-year
River Rch & RM= Elm 01 41,Reach-1,2118
      60      75      86      62      99     137     133
Boundary for River Rch & Prof#=Elm 01 41,Reach-1,1
Up Type=0
Dn Type=3
Dn Slope=0.005
Boundary for River Rch & Prof#=Elm 01 41,Reach-1,2
Up Type=0
Dn Type=3
Dn Slope=0.005
Boundary for River Rch & Prof#=Elm 01 41,Reach-1,3
Up Type=0
Dn Type=3
Dn Slope=0.005
Boundary for River Rch & Prof#=Elm 01 41,Reach-1,4
Up Type=0
Dn Type=3
Dn Slope=0.005
Boundary for River Rch & Prof#=Elm 01 41,Reach-1,5
Up Type=0
Dn Type=3
Dn Slope=0.005
Boundary for River Rch & Prof#=Elm 01 41,Reach-1,6
Up Type=0
Dn Type=3
Dn Slope=0.005
Boundary for River Rch & Prof#=Elm 01 41,Reach-1,7
Up Type=0
Dn Type=3
Dn Slope=0.005

--- Elm 01 41.g01 (geometry) ---

Geom Title=Existing Conditions

River Reach=Elm 01 41,Reach-1
Reach XY= 30
      1552505.00      6850538.00      1552506.56      6850493.87
      1552527.82      6850464.02      1552556.46      6850441.86
      1552614.67      6850427.23      1552748.97      6850296.17
      1552818.56      6850274.51      1552849.24      6850240.51
      1552863.03      6850181.64      1552902.30      6850143.36
      1553103.45      6850134.25      1553152.82      6850094.12
      1553203.28      6850083.84      1553252.82      6850044.10
      1553314.70      6850027.24      1553394.11      6849947.39
      1553408.41      6849896.04      1553420.89      6849888.52
      1553503.43      6849891.44      1553602.71      6849982.90
      1553653.29      6849984.70      1553703.12      6849944.26
      1553749.21      6849931.98      1553763.48      6849891.50
      1553848.94      6849885.62      1553910.98      6849840.36
      1554011.45      6849830.26      1554049.26      6849790.57
      1554065.78      6849728.34      1554205.00      6849588.00

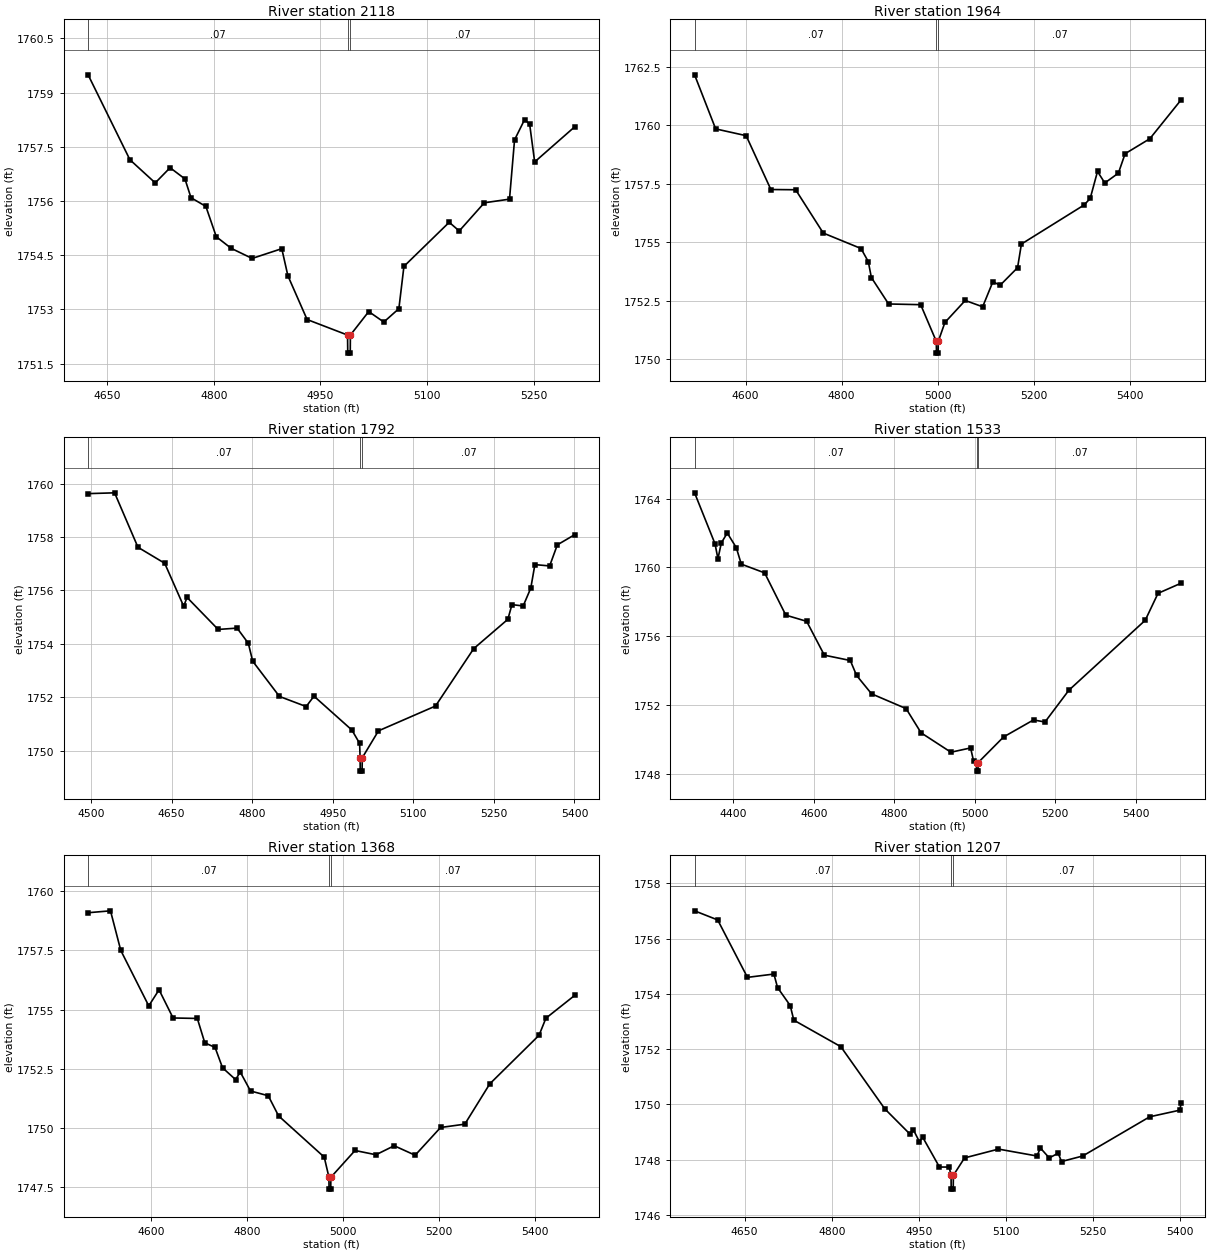
Type RM Length L Ch R = 1,2118,154,154,154
BEGIN DESCRIPTION:
Elm 01 41 2118.144
END DESCRIPTION:
XS GIS Cut Line= 3
      1552776.54      6850747.71      1552556.46      6850441.86
      1552339.54      6850223.91
#Sta/Elev= 30
  4623.2 1759.49  4682.0 1757.14  4717.6 1756.50  4738.5 1756.92  4759.4 1756.61
  4767.9 1756.09  4788.8 1755.85  4803.5 1755.01  4824.4 1754.69  4853.9 1754.41
  4895.6 1754.68  4904.2 1753.93  4931.2 1752.72  4988.1 1752.29  4988.4 1751.79
  4991.9 1751.79  4992.1 1752.29  5017.9 1752.94  5039.1 1752.65  5060.3 1753.02
  5067.4 1754.19  5131.1 1755.41  5145.2 1755.17  5180.5 1755.95  5215.9 1756.05
  5223.0 1757.69  5237.1 1758.25  5244.2 1758.13  5251.3 1757.08  5307.5 1758.05
#Mann=3,-1,0
  4623.2    0.07       0  4988.1    0.07       0  4992.1    0.07       0
Bank Sta=4988.1,4992.1
Exp/Cntr=0.3,0.1

Type RM Length L Ch R = 1,1964,172,172,172
BEGIN DESCRIPTION:
Elm 01 41 1963.601
END DESCRIPTION:
XS GIS Cut Line= 3
      1552954.99      6850787.98      1552681.82      6850361.70
      1552255.03      6850088.02
#Sta/Elev= 30
  4493.7 1762.16  4537.6 1759.85  4601.1 1759.56  4652.6 1757.26  4704.2 1757.25
  4761.7 1755.40  4840.3 1754.74  4855.5 1754.18  4861.9 1753.50  4897.8 1752.37
  4964.6 1752.34  4997.2 1750.77  4997.5 1750.27  5001.0 1750.27  5001.2 1750.77
  5015.1 1751.58  5057.4 1752.52  5093.7 1752.25  5115.0 1753.32  5130.1 1753.17
  5166.4 1753.92  5174.4 1754.93  5305.1 1756.60  5317.7 1756.88  5332.9 1758.03
  5348.1 1757.54  5376.4 1757.96  5390.4 1758.79  5441.9 1759.43  5507.0 1761.09
#Mann=3,-1,0
  4493.7    0.07       0  4997.2    0.07       0  5001.2    0.07       0
Bank Sta=4997.2,5001.2
Exp/Cntr=0.3,0.1

Type RM Length L Ch R = 1,1792,259,259,259
BEGIN DESCRIPTION:
Elm 01 41 1792.34
END DESCRIPTION:
XS GIS Cut Line= 3
      1553130.73      6850671.35      1552818.21      6850268.55
      1552519.78      6850008.29
#Sta/Elev= 30
  4494.5 1759.63  4543.8 1759.66  4587.3 1757.62  4637.1 1757.02  4672.4 1755.41
  4678.7 1755.74  4736.6 1754.54  4771.9 1754.59  4792.8 1754.02  4800.9 1753.35
  4850.7 1752.03  4900.5 1751.65  4915.0 1752.04  4985.6 1750.77  5000.0 1750.27
  5000.9 1749.73  5001.1 1749.23  5004.6 1749.23  5004.9 1749.73  5035.1 1750.74
  5141.3 1751.67  5212.4 1753.82  5276.0 1754.92  5283.6 1755.47  5304.5 1755.42
  5318.7 1756.09  5326.3 1756.97  5353.8 1756.92  5368.1 1757.71  5400.3 1758.09
#Mann=3,-1,0
  4494.5    0.07       0  5000.9    0.07       0  5004.9    0.07       0
Bank Sta=5000.9,5004.9
Exp/Cntr=0.3,0.1

Type RM Length L Ch R = 1,1533,165,165,165
BEGIN DESCRIPTION:
Elm 01 41 1533.385
END DESCRIPTION:
XS GIS Cut Line= 3
      1553355.01      6850738.01      1553002.47      6850138.02
      1552554.98      6849887.99
#Sta/Elev= 30
  4304.1 1764.34  4354.9 1761.37  4362.1 1760.50  4370.6 1761.43  4385.3 1762.00
  4407.7 1761.15  4420.1 1760.19  4478.1 1759.68  4530.7 1757.22  4582.5 1756.86
  4626.4 1754.89  4690.9 1754.58  4706.5 1753.71  4743.7 1752.64  4829.5 1751.78
  4866.7 1750.37  4940.9 1749.24  4989.7 1749.49  4997.1 1748.73  5004.6 1748.64
  5004.8 1748.14  5008.3 1748.14  5008.6 1748.64  5071.7 1750.13  5146.0 1751.12
  5174.5 1751.00  5233.9 1752.85  5423.5 1756.92  5455.3 1758.49  5512.6 1759.08
#Mann=3,-1,0
  4304.1    0.07       0  5004.6    0.07       0  5008.6    0.07       0
Bank Sta=5004.6,5008.6
Exp/Cntr=0.3,0.1

Type RM Length L Ch R = 1,1368,161,161,161
BEGIN DESCRIPTION:
Elm 01 41 1368.487
END DESCRIPTION:
XS GIS Cut Line= 3
      1553425.84      6850549.79      1553152.82      6850094.12
      1552729.97      6849862.98
#Sta/Elev= 30
  4468.8 1759.09  4515.4 1759.17  4536.8 1757.50  4595.1 1755.16  4616.5 1755.84
  4645.7 1754.65  4696.2 1754.63  4711.8 1753.60  4733.1 1753.41  4748.7 1752.55
  4775.9 1752.05  4785.6 1752.37  4807.0 1751.57  4843.9 1751.37  4865.4 1750.52
  4960.5 1748.78  4970.3 1747.93  4970.5 1747.43  4974.0 1747.43  4974.3 1747.93
  5024.6 1749.06  5068.2 1748.88  5106.2 1749.26  5149.8 1748.86  5202.7 1750.03
  5253.2 1750.17  5305.2 1751.87  5407.8 1753.92  5422.1 1754.64  5481.9 1755.60
#Mann=3,-1,0
  4468.8    0.07       0  4970.3    0.07       0  4974.3    0.07       0
Bank Sta=4970.3,4974.3
Exp/Cntr=0.3,0.1

Type RM Length L Ch R = 1,1207,199,199,199
BEGIN DESCRIPTION:
Elm 01 41 1206.535
END DESCRIPTION:
XS GIS Cut Line= 3
      1553509.17      6850417.83      1553298.97      6850035.50
      1552958.53      6849821.53
#Sta/Elev= 30
  4563.7 1757.01  4603.5 1756.68  4654.8 1754.60  4700.4 1754.72  4706.7 1754.23
  4728.5 1753.58  4734.7 1753.05  4815.7 1752.09  4891.4 1749.84  4935.0 1748.92
  4940.7 1749.08  4951.1 1748.65  4956.8 1748.81  4985.7 1747.73  5002.4 1747.73
  5005.7 1747.43  5005.9 1746.93  5009.4 1746.93  5009.7 1747.43  5028.9 1748.06
  5087.4 1748.38  5153.7 1748.13  5159.6 1748.42  5174.9 1748.06  5190.2 1748.23
  5196.1 1747.93  5232.6 1748.13  5348.0 1749.55  5399.9 1749.79  5402.1 1750.04
#Mann=3,-1,0
  4563.7    0.07       0  5005.7    0.07       0  5009.7    0.07       0
Bank Sta=5005.7,5009.7
Exp/Cntr=0.3,0.1

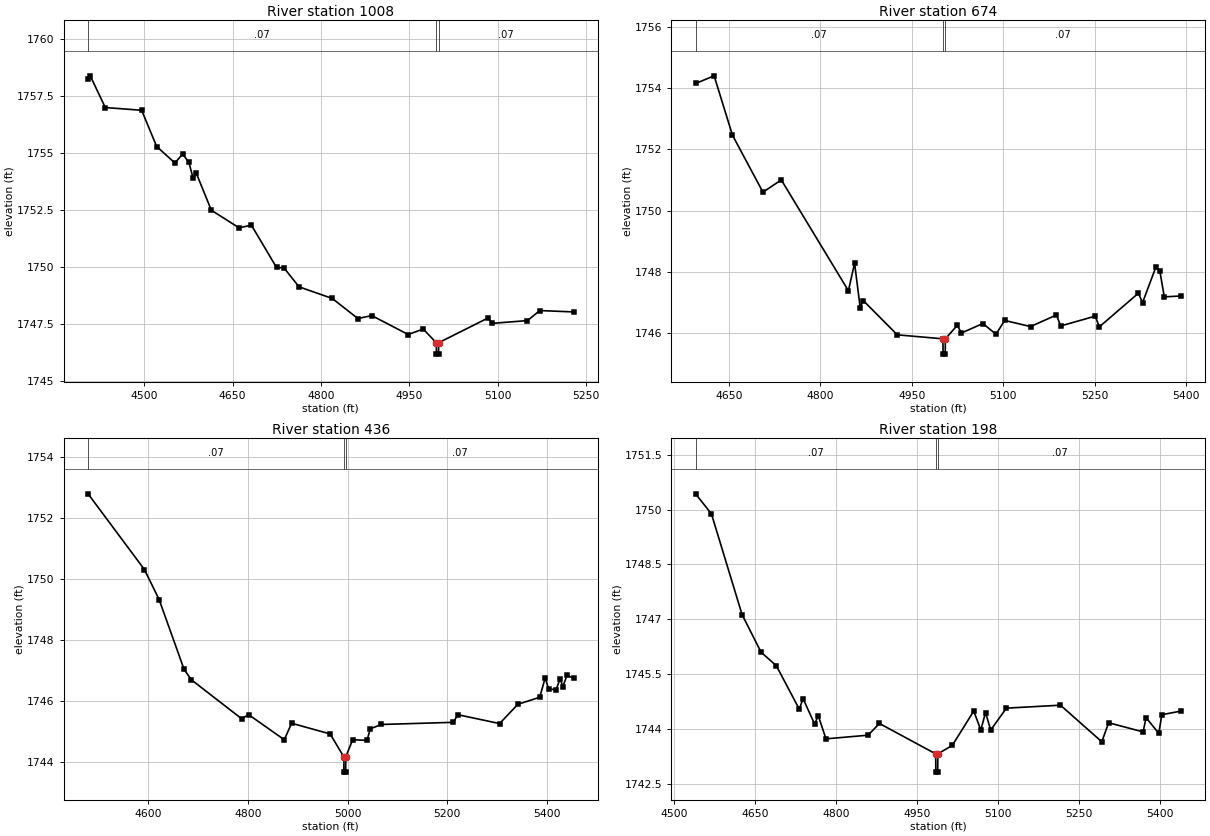
Type RM Length L Ch R = 1,1008,334,334,334
BEGIN DESCRIPTION:
Elm 01 41 1007.734
END DESCRIPTION:
XS GIS Cut Line= 3
      1553620.29      6850449.11      1553420.89      6849888.52
      1553229.97      6849762.98
#Sta/Elev= 30
  4405.0 1758.24  4408.7 1758.39  4434.2 1757.00  4495.9 1756.88  4521.4 1755.29
  4552.3 1754.57  4565.4 1754.96  4576.0 1754.60  4583.1 1753.90  4588.4 1754.13
  4614.0 1752.50  4660.9 1751.73  4682.1 1751.84  4724.6 1749.99  4737.3 1749.97
  4762.8 1749.14  4819.2 1748.63  4862.6 1747.75  4886.2 1747.88  4947.9 1747.05
  4973.4 1747.29  4995.6 1746.69  4995.9 1746.19  4999.4 1746.19  4999.6 1746.69
  5083.8 1747.78  5090.8 1747.54  5150.2 1747.66  5171.2 1748.10  5228.5 1748.04
#Mann=3,-1,0
  4405.0    0.07       0  4995.6    0.07       0  4999.6    0.07       0
Bank Sta=4995.6,4999.6
Exp/Cntr=0.3,0.1

Type RM Length L Ch R = 1,674,238,238,238
BEGIN DESCRIPTION:
Elm 01 41 673.893
END DESCRIPTION:
XS GIS Cut Line= 3
      1553724.46      6850348.39      1553703.12      6849944.26
      1553415.44      6849678.27
#Sta/Elev= 30
  4595.3 1754.15  4625.7 1754.40  4655.8 1752.46  4705.8 1750.60  4735.9 1751.00
  4846.0 1747.38  4856.1 1748.28  4865.3 1746.83  4870.3 1747.06  4926.2 1745.94
  5001.0 1745.81  5001.3 1745.31  5004.8 1745.31  5005.0 1745.81  5024.6 1746.25
  5031.4 1746.00  5066.6 1746.31  5088.1 1745.96  5102.3 1746.41  5144.8 1746.21
  5187.3 1746.59  5194.1 1746.23  5250.8 1746.55  5257.6 1746.20  5321.7 1747.30
  5328.5 1746.99  5350.1 1748.14  5356.9 1748.02  5364.2 1747.18  5391.8 1747.21
#Mann=3,-1,0
  4595.3    0.07       0  5001.0    0.07       0  5005.0    0.07       0
Bank Sta=5001,5005
Exp/Cntr=0.3,0.1

Type RM Length L Ch R = 1,436,238,238,238
BEGIN DESCRIPTION:
Elm 01 41 437.199
END DESCRIPTION:
XS GIS Cut Line= 3
      1554203.61      6850268.52      1553898.31      6849848.85
      1553482.97      6849662.98
#Sta/Elev= 30
  4479.3 1752.79  4592.4 1750.31  4621.8 1749.33  4672.0 1747.04  4686.7 1746.70
  4787.2 1745.43  4801.5 1745.56  4872.9 1744.74  4887.6 1745.28  4964.9 1744.93
  4992.3 1744.18  4992.5 1743.68  4996.0 1743.68  4996.3 1744.18  5010.0 1744.74
  5038.7 1744.72  5045.7 1745.10  5067.6 1745.24  5212.0 1745.31  5221.0 1745.56
  5304.8 1745.27  5341.5 1745.90  5385.3 1746.13  5396.3 1746.77  5403.0 1746.40
  5418.2 1746.38  5426.2 1746.74  5431.7 1746.48  5440.1 1746.85  5453.3 1746.75
#Mann=3,-1,0
  4479.3    0.07       0  4992.3    0.07       0  4996.3    0.07       0
Bank Sta=4992.3,4996.3
Exp/Cntr=0.3,0.1

Type RM Length L Ch R = 1,198,0,0,0
BEGIN DESCRIPTION:
Elm 01 41 197.678
END DESCRIPTION:
XS GIS Cut Line= 3
      1554384.17      6850060.20      1554065.78      6849728.34
      1553661.42      6849557.15
#Sta/Elev= 30
  4540.1 1750.43  4569.5 1749.88  4626.1 1747.13  4661.3 1746.10  4689.6 1745.73
  4732.1 1744.54  4739.0 1744.83  4760.4 1744.14  4767.3 1744.36  4781.5 1743.73
  4859.4 1743.83  4880.5 1744.15  4984.6 1743.32  4984.9 1742.82  4988.4 1742.82
  4988.6 1743.32  5015.4 1743.55  5055.1 1744.49  5068.2 1743.97  5076.9 1744.45
  5086.5 1743.97  5115.6 1744.57  5215.7 1744.65  5292.2 1743.65  5304.9 1744.17
  5368.7 1743.92  5374.1 1744.31  5397.8 1743.88  5403.3 1744.39  5439.1 1744.49
#Mann=3,-1,0
  4540.1    0.07       0  4984.6    0.07       0  4988.6    0.07       0
Bank Sta=4984.6,4988.6
Exp/Cntr=0.3,0.1

Chan Stop Cuts=-1