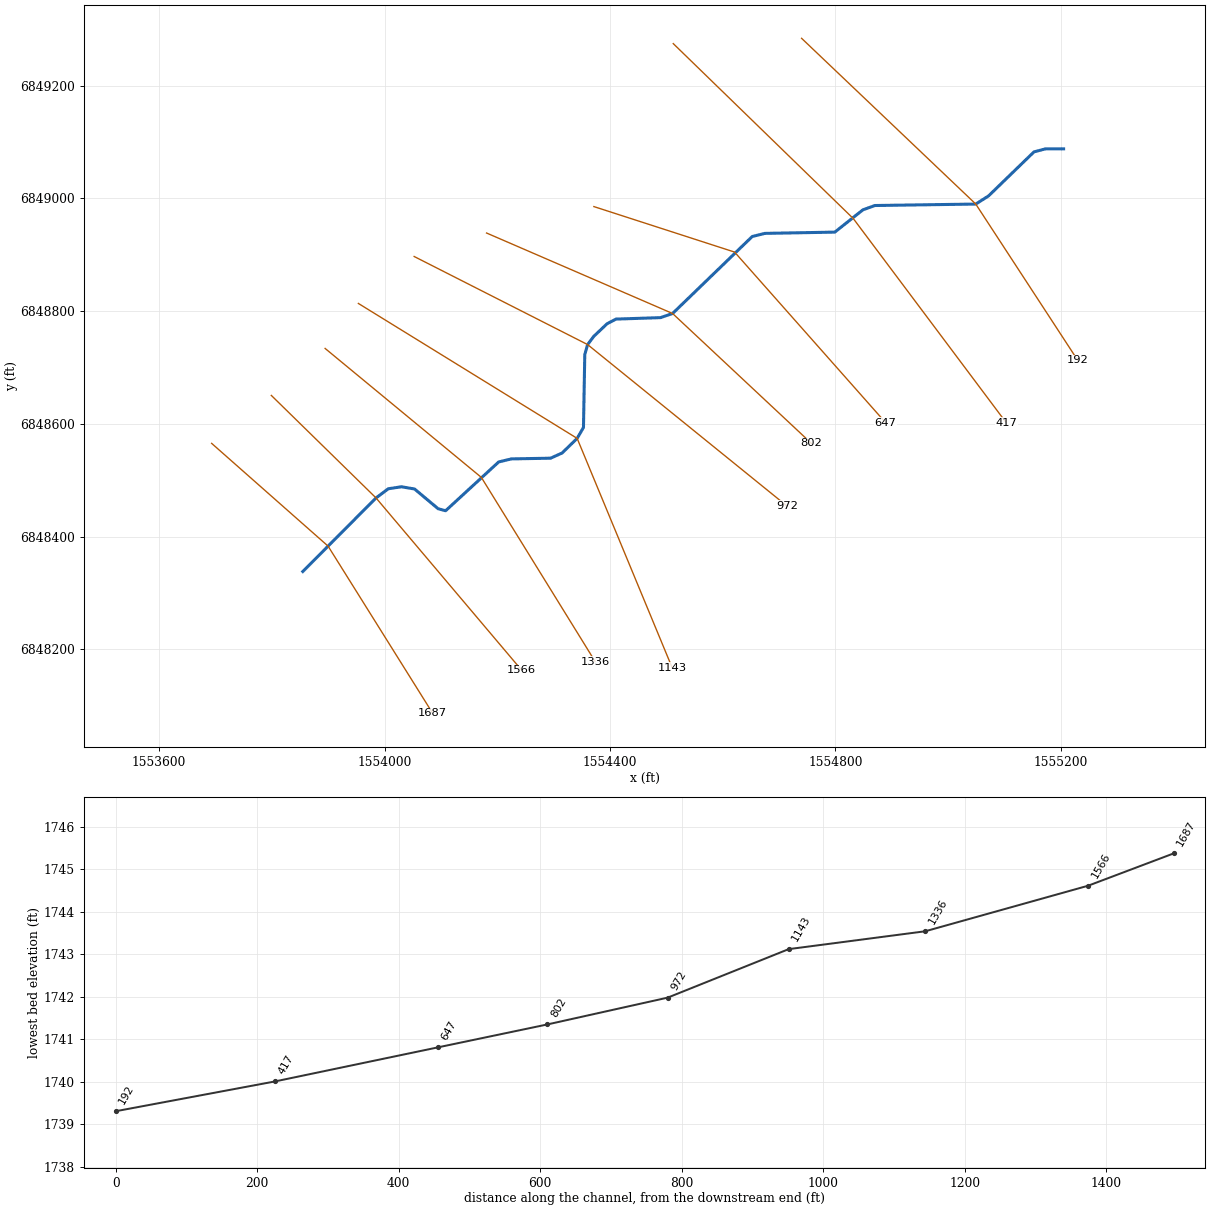
--- Elm 01 42.prj (project) ---

Proj Title=Elm 01 42 Base Level Engineering
Current Plan=p01
Default Exp/Contr=0.3,0.1
English Units
Geom File=g01
Flow File=f01
Plan File=p01
BEGIN DESCRIPTION:
Elm 01 42
END DESCRIPTION:

--- Elm 01 42.p01 (plan) ---

Plan Title=Multiple Run
Short Identifier=Multiple
Geom File=g01
Flow File=f01
Subcritical Flow
K Sum by GR= 0
Std Step Tol= 0.01
Critical Tol= 0.01
Num of Std Step Trials= 20
Max Error Tol= 0.3
Flow Tol Ratio= 0.001
Split Flow NTrial= 30
Split Flow Tol= 0.02
Split Flow Ratio= 0.02
Log Output Level= 0
Friction Slope Method= 1
Unsteady Friction Slope Method= 2
Unsteady Bridges Friction Slope Method= 1
Parabolic Critical Depth
Global Vel Dist=  1 , 1 , 1
Global Log Level= 0
CheckData=True
Encroach Param= -1, 0, 0, 0
BEGIN DESCRIPTION:
Multiple Run
END DESCRIPTION:

--- Elm 01 42.f01 (steady flow) ---

Flow Title=Multiple
Number of Profiles=7
Profile Names=10-year,25-year,50-year,1pct_min,100-year,1pct_plu,500-year
River Rch & RM= Elm 01 42,Reach-1,1687
      73      93     108      78     125     172     170
Boundary for River Rch & Prof#=Elm 01 42,Reach-1,1
Up Type=0
Dn Type=3
Dn Slope=0.005
Boundary for River Rch & Prof#=Elm 01 42,Reach-1,2
Up Type=0
Dn Type=3
Dn Slope=0.005
Boundary for River Rch & Prof#=Elm 01 42,Reach-1,3
Up Type=0
Dn Type=3
Dn Slope=0.005
Boundary for River Rch & Prof#=Elm 01 42,Reach-1,4
Up Type=0
Dn Type=3
Dn Slope=0.005
Boundary for River Rch & Prof#=Elm 01 42,Reach-1,5
Up Type=0
Dn Type=3
Dn Slope=0.005
Boundary for River Rch & Prof#=Elm 01 42,Reach-1,6
Up Type=0
Dn Type=3
Dn Slope=0.005
Boundary for River Rch & Prof#=Elm 01 42,Reach-1,7
Up Type=0
Dn Type=3
Dn Slope=0.005

--- Elm 01 42.g01 (geometry) ---

Geom Title=Existing Conditions

River Reach=Elm 01 42,Reach-1
Reach XY= 30
      1553855.00      6848338.00      1553984.91      6848468.58
      1554006.65      6848484.85      1554030.00      6848488.40
      1554053.35      6848484.41      1554095.13      6848449.39
      1554108.40      6848445.84      1554202.58      6848532.44
      1554225.06      6848537.85      1554294.69      6848539.10
      1554315.16      6848548.36      1554341.80      6848574.27
      1554353.02      6848593.65      1554355.34      6848722.97
      1554360.35      6848740.73      1554371.24      6848755.22
      1554394.84      6848777.64      1554410.69      6848785.93
      1554489.78      6848788.53      1554511.17      6848795.86
      1554652.55      6848932.53      1554674.99      6848938.02
      1554799.06      6848940.27      1554848.94      6848979.86
      1554870.22      6848987.48      1555049.15      6848990.06
      1555071.76      6849004.44      1555152.49      6849082.67
      1555173.12      6849088.07      1555205.00      6849088.00

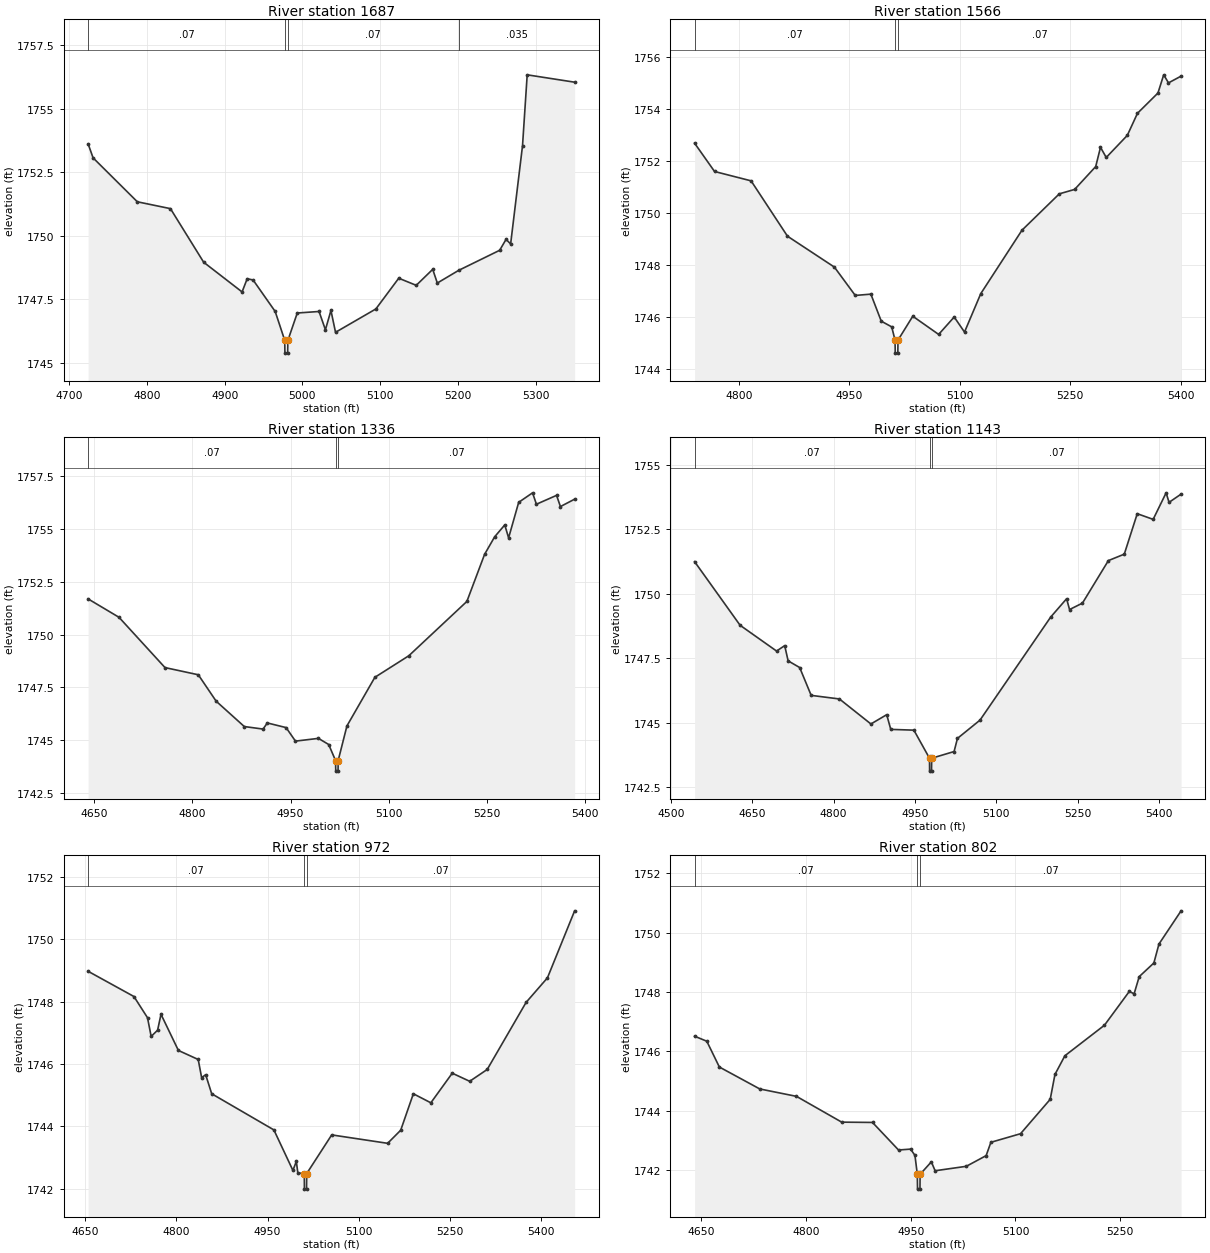
Type RM Length L Ch R = 1,1687,121,121,121
BEGIN DESCRIPTION:
Elm 01 42 1686.708
END DESCRIPTION:
XS GIS Cut Line= 3
      1553693.20      6848565.43      1553899.83      6848383.06
      1554085.55      6848086.28
#Sta/Elev= 30
  4724.4 1753.61  4730.8 1753.06  4787.7 1751.33  4830.3 1751.06  4873.0 1748.95
  4922.4 1747.78  4929.0 1748.30  4936.6 1748.25  4965.0 1747.01  4977.3 1745.87
  4977.5 1745.37  4981.0 1745.37  4981.3 1745.87  4993.4 1746.95  5021.4 1747.01
  5029.6 1746.29  5036.7 1747.05  5042.6 1746.19  5094.5 1747.11  5123.9 1748.32
  5146.4 1748.04  5167.6 1748.67  5173.5 1748.13  5201.0 1748.63  5253.7 1749.42
  5261.9 1749.85  5267.8 1749.67  5283.1 1753.54  5289.1 1756.33  5350.1 1756.04
#Mann=4,-1,0
  4724.4    0.07       0  4977.3    0.07       0  4981.3    0.07       0
  5201.0   0.035       0
Bank Sta=4977.3,4981.3
Exp/Cntr=0.3,0.1

Type RM Length L Ch R = 1,1566,230,230,230
BEGIN DESCRIPTION:
Elm 01 42 1566.083
END DESCRIPTION:
XS GIS Cut Line= 3
      1553799.13      6848650.47      1553984.91      6848468.58
      1554243.42      6848162.81
#Sta/Elev= 30
  4740.0 1752.69  4767.1 1751.60  4816.7 1751.24  4866.1 1749.11  4929.8 1747.92
  4958.1 1746.83  4979.3 1746.88  4993.4 1745.84  5007.6 1745.62  5012.1 1745.11
  5012.4 1744.61  5015.9 1744.61  5016.1 1745.11  5036.2 1746.03  5071.3 1745.33
  5092.4 1746.00  5106.4 1745.42  5128.5 1746.90  5184.4 1749.34  5235.1 1750.74
  5255.9 1750.91  5284.5 1751.79  5291.0 1752.53  5298.8 1752.14  5327.4 1752.99
  5341.2 1753.84  5369.0 1754.62  5376.8 1755.32  5383.3 1755.01  5400.4 1755.27
#Mann=3,-1,0
  4740.0    0.07       0  5012.1    0.07       0  5016.1    0.07       0
Bank Sta=5012.1,5016.1
Exp/Cntr=0.3,0.1

Type RM Length L Ch R = 1,1336,193,193,193
BEGIN DESCRIPTION:
Elm 01 42 1336.348
END DESCRIPTION:
XS GIS Cut Line= 3
      1553894.56      6848733.86      1554171.82      6848505.01
      1554373.75      6848178.28
#Sta/Elev= 30
  4640.5 1751.69  4687.7 1750.82  4758.0 1748.44  4808.9 1748.10  4836.2 1746.85
  4879.2 1745.65  4907.9 1745.53  4914.4 1745.82  4943.1 1745.60  4957.4 1744.96
  4992.5 1745.09  5008.2 1744.80  5018.7 1744.04  5019.0 1743.54  5022.5 1743.54
  5022.7 1744.04  5036.1 1745.68  5078.8 1747.98  5130.7 1749.00  5219.4 1751.57
  5246.5 1753.80  5261.9 1754.63  5277.3 1755.19  5283.2 1754.58  5298.6 1756.26
  5319.8 1756.71  5325.7 1756.17  5356.5 1756.59  5362.4 1756.06  5384.1 1756.41
#Mann=3,-1,0
  4640.5    0.07       0  5018.7    0.07       0  5022.7    0.07       0
Bank Sta=5018.7,5022.7
Exp/Cntr=0.3,0.1

Type RM Length L Ch R = 1,1143,171,171,171
BEGIN DESCRIPTION:
Elm 01 42 1142.666
END DESCRIPTION:
XS GIS Cut Line= 3
      1553953.60      6848813.70      1554341.80      6848574.27
      1554510.46      6848167.23
#Sta/Elev= 30
  4543.9 1751.25  4627.8 1748.78  4695.0 1747.78  4710.0 1747.99  4716.3 1747.40
  4737.6 1747.14  4758.8 1746.06  4810.9 1745.92  4868.9 1744.95  4898.0 1745.31
  4905.5 1744.74  4948.1 1744.71  4976.9 1743.62  4977.1 1743.12  4980.6 1743.12
  4980.9 1743.62  5022.2 1743.88  5028.4 1744.39  5070.0 1745.10  5200.3 1749.10
  5229.6 1749.81  5235.0 1749.39  5258.8 1749.64  5306.6 1751.29  5335.9 1751.54
  5359.8 1753.11  5389.1 1752.89  5413.0 1753.92  5418.4 1753.55  5440.6 1753.87
#Mann=3,-1,0
  4543.9    0.07       0  4976.9    0.07       0  4980.9    0.07       0
Bank Sta=4976.9,4980.9
Exp/Cntr=0.3,0.1

Type RM Length L Ch R = 1,972,170,170,170
BEGIN DESCRIPTION:
Elm 01 42 972.475
END DESCRIPTION:
XS GIS Cut Line= 3
      1554052.56      6848897.03      1554360.35      6848740.73
      1554714.02      6848454.32
#Sta/Elev= 30
  4654.8 1748.97  4730.2 1748.16  4752.5 1747.48  4758.5 1746.88  4769.1 1747.08
  4774.7 1747.59  4803.3 1746.43  4835.9 1746.14  4841.5 1745.56  4848.2 1745.65
  4858.1 1745.04  4960.4 1743.88  4991.7 1742.58  4997.3 1742.87  4999.8 1742.50
  5010.4 1742.48  5010.6 1741.98  5014.1 1741.98  5014.4 1742.48  5055.5 1743.72
  5147.5 1743.45  5169.0 1743.87  5189.8 1745.04  5218.6 1744.75  5253.8 1745.70
  5282.5 1745.44  5311.3 1745.82  5375.2 1747.97  5410.4 1748.76  5455.1 1750.91
#Mann=3,-1,0
  4654.8    0.07       0  5010.4    0.07       0  5014.4    0.07       0
Bank Sta=5010.4,5014.4
Exp/Cntr=0.3,0.1

Type RM Length L Ch R = 1,802,155,155,155
BEGIN DESCRIPTION:
Elm 01 42 802.167
END DESCRIPTION:
XS GIS Cut Line= 3
      1554181.04      6848938.69      1554511.17      6848795.86
      1554757.46      6848565.40
#Sta/Elev= 30
  4640.3 1746.51  4657.8 1746.34  4675.8 1745.47  4733.7 1744.73  4786.3 1744.48
  4851.1 1743.61  4895.2 1743.60  4932.5 1742.67  4949.7 1742.70  4956.0 1742.49
  4959.4 1741.85  4959.7 1741.35  4963.2 1741.35  4963.4 1741.85  4979.5 1742.27
  4984.9 1741.97  5029.6 1742.12  5058.0 1742.48  5064.8 1742.93  5107.3 1743.22
  5149.8 1744.38  5156.6 1745.22  5170.8 1745.85  5227.5 1746.88  5263.1 1748.02
  5270.0 1747.94  5277.3 1748.52  5298.3 1748.98  5305.6 1749.62  5337.3 1750.74
#Mann=3,-1,0
  4640.3    0.07       0  4959.4    0.07       0  4963.4    0.07       0
Bank Sta=4959.4,4963.4
Exp/Cntr=0.3,0.1

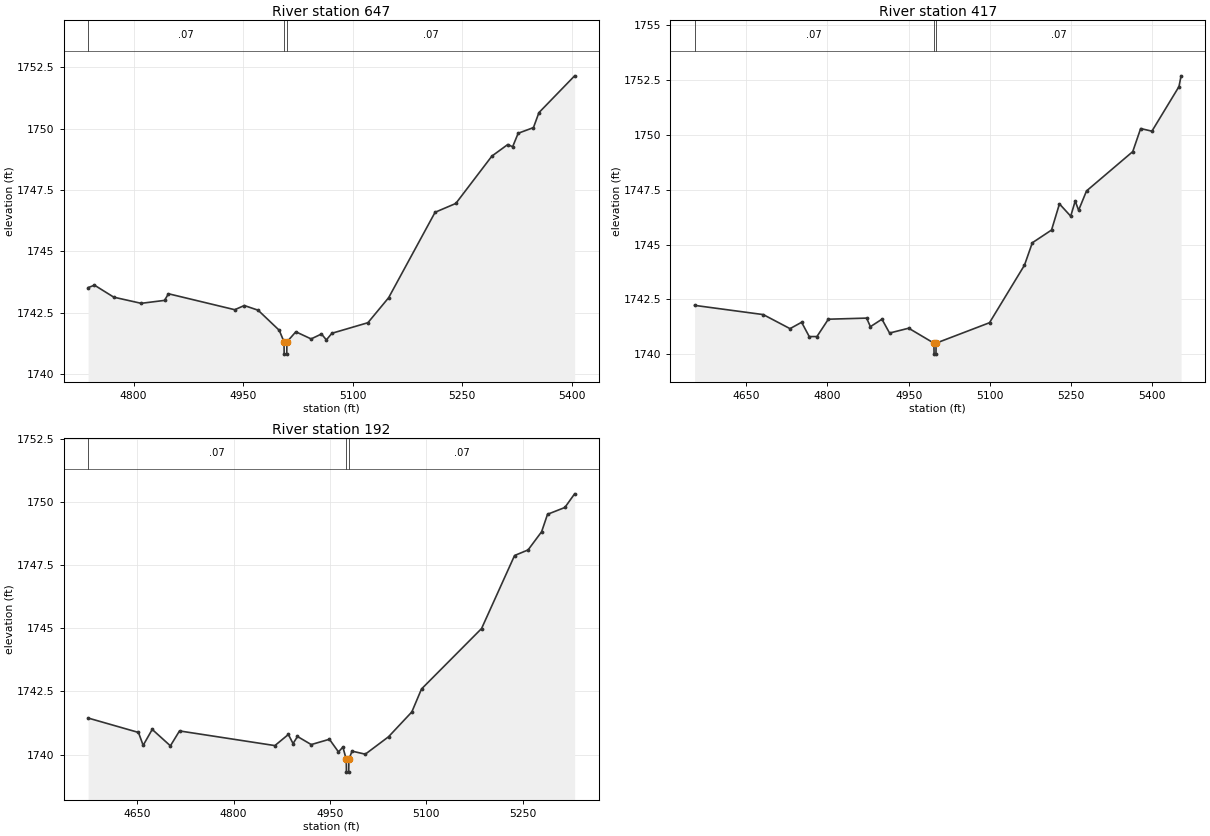
Type RM Length L Ch R = 1,647,230,230,230
BEGIN DESCRIPTION:
Elm 01 42 647.311
END DESCRIPTION:
XS GIS Cut Line= 3
      1554371.50      6848985.58      1554621.17      6848904.86
      1554888.90      6848602.43
#Sta/Elev= 30
  4737.6 1743.52  4746.3 1743.62  4772.8 1743.13  4810.3 1742.88  4842.3 1743.00
  4847.6 1743.27  4938.4 1742.62  4951.5 1742.79  4970.4 1742.60  4999.4 1741.78
  5005.9 1741.31  5006.1 1740.81  5009.6 1740.81  5009.9 1741.31  5022.1 1741.72
  5043.0 1741.43  5057.2 1741.63  5063.9 1741.39  5071.5 1741.66  5120.8 1742.09
  5149.2 1743.11  5212.8 1746.59  5241.2 1746.95  5290.6 1748.88  5312.3 1749.35
  5319.0 1749.26  5326.6 1749.81  5347.5 1750.04  5355.0 1750.65  5403.9 1752.15
#Mann=3,-1,0
  4737.6    0.07       0  5005.9    0.07       0  5009.9    0.07       0
Bank Sta=5005.9,5009.9
Exp/Cntr=0.3,0.1

Type RM Length L Ch R = 1,417,225,225,225
BEGIN DESCRIPTION:
Elm 01 42 417.191
END DESCRIPTION:
XS GIS Cut Line= 3
      1554512.37      6849274.76      1554831.79      6848964.36
      1555103.59      6848601.58
#Sta/Elev= 30
  4554.6 1742.23  4681.5 1741.81  4730.9 1741.17  4752.3 1741.46  4766.4 1740.81
  4780.6 1740.81  4801.7 1741.60  4872.4 1741.65  4879.4 1741.26  4900.7 1741.60
  4914.8 1740.97  4950.1 1741.19  4996.7 1740.51  4997.0 1740.01  5000.5 1740.01
  5000.7 1740.51  5099.4 1741.44  5164.0 1744.06  5178.5 1745.08  5214.0 1745.66
  5228.6 1746.85  5249.4 1746.29  5257.7 1746.98  5264.0 1746.56  5278.6 1747.44
  5364.0 1749.23  5378.6 1750.28  5399.4 1750.16  5449.4 1752.19  5453.3 1752.68
#Mann=3,-1,0
  4554.6    0.07       0  4996.7    0.07       0  5000.7    0.07       0
Bank Sta=4996.7,5000.7
Exp/Cntr=0.3,0.1

Type RM Length L Ch R = 1,192,0,0,0
BEGIN DESCRIPTION:
Elm 01 42 192.419
END DESCRIPTION:
XS GIS Cut Line= 3
      1554740.11      6849284.14      1555049.15      6848990.06
      1555230.02      6848712.97
#Sta/Elev= 30
  4573.4 1741.45  4651.8 1740.88  4659.1 1740.37  4673.2 1741.00  4701.5 1740.35
  4715.7 1740.94  4864.2 1740.36  4885.2 1740.80  4892.5 1740.44  4899.4 1740.72
  4920.8 1740.40  4949.1 1740.61  4963.2 1740.11  4970.1 1740.30  4975.4 1739.81
  4975.6 1739.31  4979.1 1739.31  4979.4 1739.81  4984.3 1740.14  5005.0 1740.02
  5041.2 1740.71  5077.4 1741.69  5092.5 1742.60  5186.0 1744.99  5237.4 1747.88
  5258.4 1748.10  5279.5 1748.82  5288.7 1749.51  5315.7 1749.78  5330.9 1750.32
#Mann=3,-1,0
  4573.4    0.07       0  4975.4    0.07       0  4979.4    0.07       0
Bank Sta=4975.4,4979.4
Exp/Cntr=0.3,0.1

Chan Stop Cuts=-1