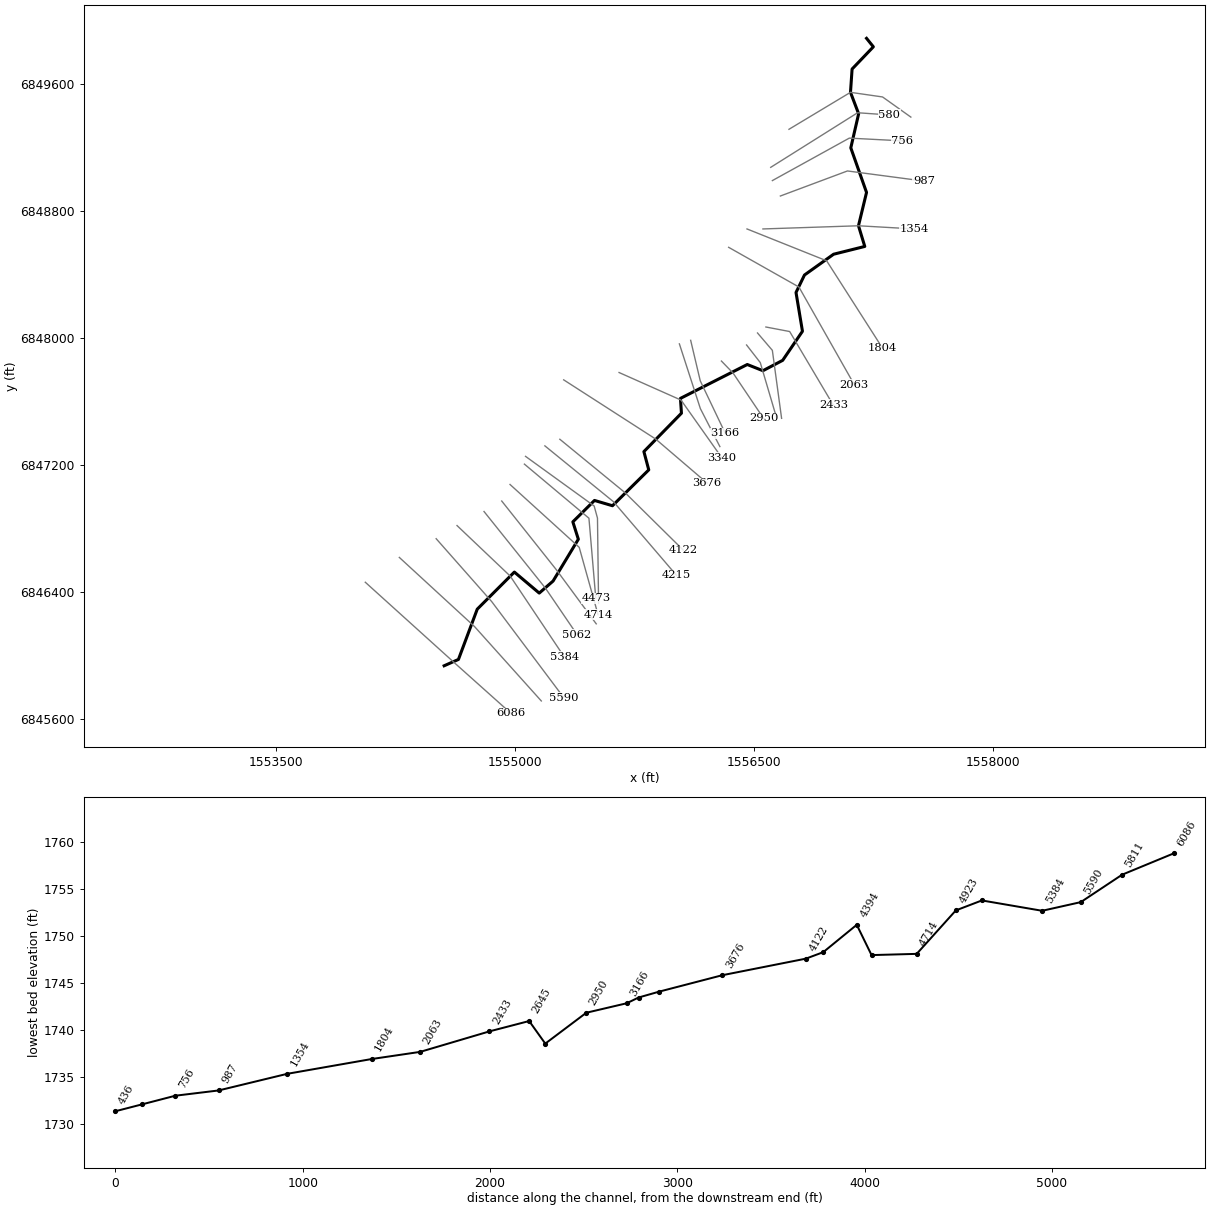
--- Elm 01 43.prj (project) ---

Proj Title=Elm 01 43 Base Level Engineering
Current Plan=p01
Default Exp/Contr=0.3,0.1
English Units
Geom File=g01
Flow File=f01
Plan File=p01
BEGIN DESCRIPTION:
Elm 01 43
END DESCRIPTION:

--- Elm 01 43.p01 (plan) ---

Plan Title=Multiple Run
Short Identifier=Multiple
Geom File=g01
Flow File=f01
Subcritical Flow
K Sum by GR= 0
Std Step Tol= 0.01
Critical Tol= 0.01
Num of Std Step Trials= 20
Max Error Tol= 0.3
Flow Tol Ratio= 0.001
Split Flow NTrial= 30
Split Flow Tol= 0.02
Split Flow Ratio= 0.02
Log Output Level= 0
Friction Slope Method= 1
Unsteady Friction Slope Method= 2
Unsteady Bridges Friction Slope Method= 1
Parabolic Critical Depth
Global Vel Dist=  1 , 1 , 1
Global Log Level= 0
CheckData=True
Encroach Param= -1, 0, 0, 0
BEGIN DESCRIPTION:
Multiple Run
END DESCRIPTION:

--- Elm 01 43.f01 (steady flow) ---

Flow Title=Multiple
Number of Profiles=7
Profile Names=10-year,25-year,50-year,1pct_min,100-year,1pct_plu,500-year
River Rch & RM= Elm 01 43,Reach-1,6086
      89     115     134      98     157     215     215
Boundary for River Rch & Prof#=Elm 01 43,Reach-1,1
Up Type=0
Dn Type=3
Dn Slope=0.005
Boundary for River Rch & Prof#=Elm 01 43,Reach-1,2
Up Type=0
Dn Type=3
Dn Slope=0.005
Boundary for River Rch & Prof#=Elm 01 43,Reach-1,3
Up Type=0
Dn Type=3
Dn Slope=0.005
Boundary for River Rch & Prof#=Elm 01 43,Reach-1,4
Up Type=0
Dn Type=3
Dn Slope=0.005
Boundary for River Rch & Prof#=Elm 01 43,Reach-1,5
Up Type=0
Dn Type=3
Dn Slope=0.005
Boundary for River Rch & Prof#=Elm 01 43,Reach-1,6
Up Type=0
Dn Type=3
Dn Slope=0.005
Boundary for River Rch & Prof#=Elm 01 43,Reach-1,7
Up Type=0
Dn Type=3
Dn Slope=0.005

--- Elm 01 43.g01 (geometry) ---

Geom Title=Existing Conditions

River Reach=Elm 01 43,Reach-1
Reach XY= 30
      1554555.00      6845938.00      1554644.74      6845977.90
      1554762.75      6846294.45      1554995.56      6846527.95
      1555151.66      6846395.58      1555238.35      6846471.25
      1555396.93      6846734.69      1555362.50      6846844.05
      1555498.27      6846978.85      1555611.05      6846945.50
      1555838.70      6847171.30      1555808.16      6847286.35
      1556043.75      6847528.01      1556037.47      6847621.35
      1556456.74      6847834.63      1556555.00      6847795.56
      1556678.84      6847860.85      1556802.94      6848043.86
      1556762.53      6848288.01      1556815.62      6848398.00
      1556998.28      6848528.83      1557193.91      6848577.91
      1557154.42      6848708.04      1557204.95      6848917.96
      1557106.21      6849198.51      1557155.40      6849413.00
      1557104.27      6849548.07      1557114.30      6849694.67
      1557247.75      6849834.67      1557205.00      6849888.00

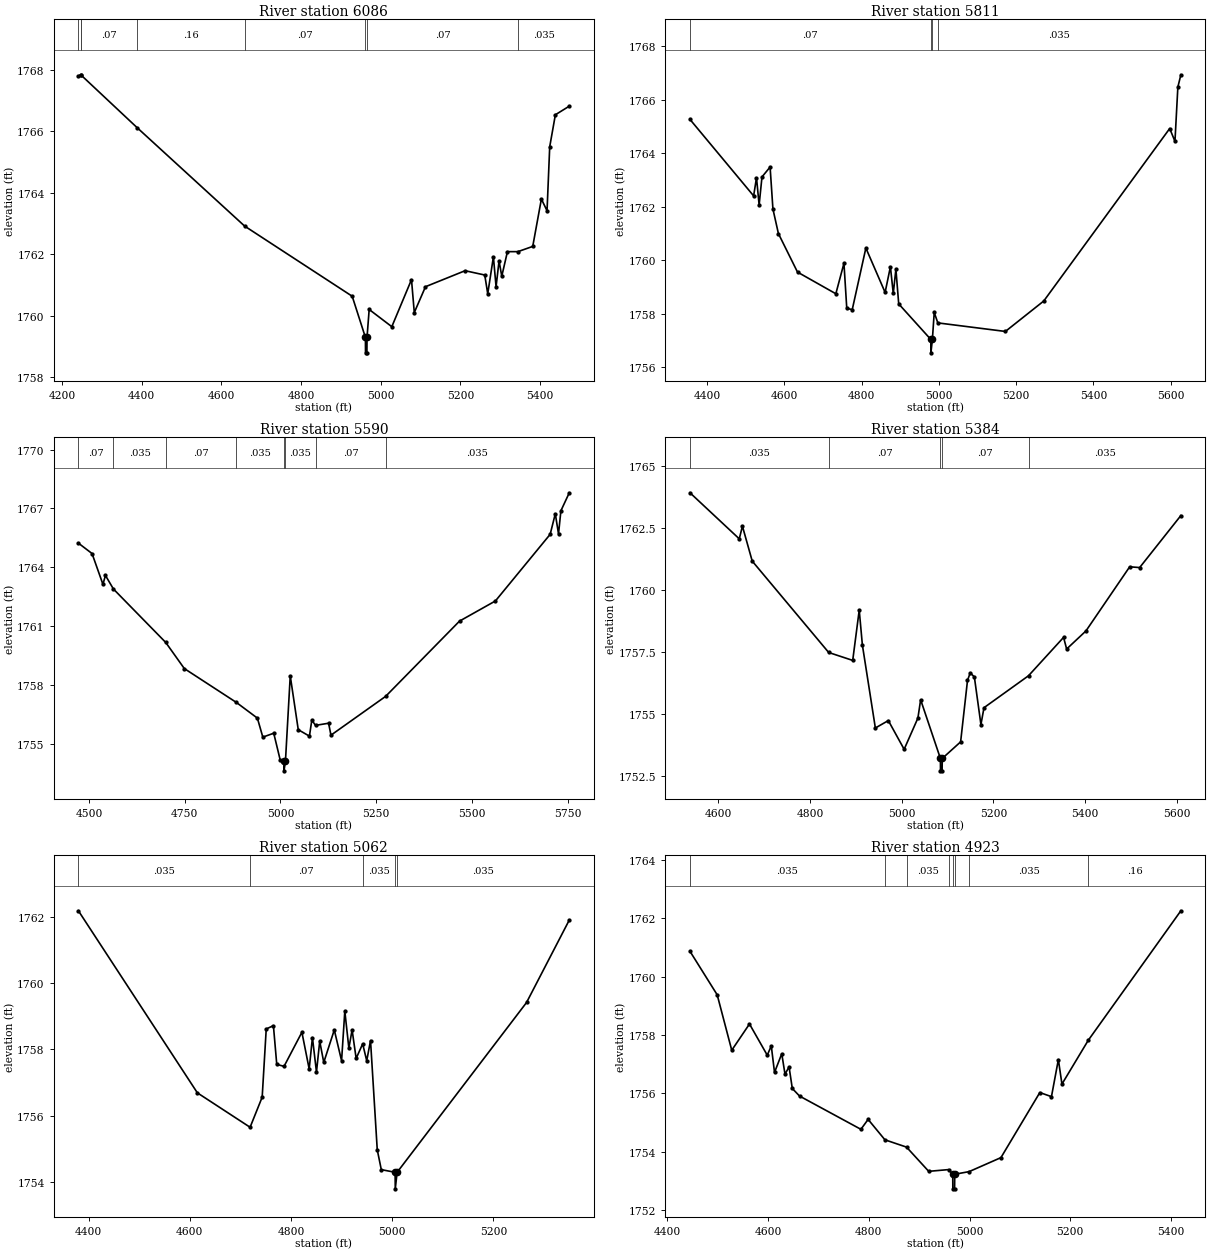
Type RM Length L Ch R = 1,6086,275,275,275
BEGIN DESCRIPTION:
Elm 01 43 6085.621
END DESCRIPTION:
XS GIS Cut Line= 3
      1554060.37      6846463.88      1554622.34      6845954.31
      1554974.45      6845638.34
#Sta/Elev= 30
  4241.4 1767.79  4247.2 1767.83  4247.3 1767.83  4388.8 1766.11  4658.6 1762.91
  4928.4 1760.63  4961.6 1759.29  4961.8 1758.79  4965.3 1758.79  4965.6 1759.29
  4971.0 1760.20  5027.8 1759.64  5077.2 1761.17  5084.2 1760.10  5112.3 1760.94
  5211.7 1761.46  5261.0 1761.32  5268.5 1760.71  5282.7 1761.91  5289.4 1760.94
  5296.9 1761.78  5303.7 1761.28  5317.9 1762.08  5344.2 1762.08  5381.4 1762.25
  5403.1 1763.79  5417.3 1763.41  5424.0 1765.49  5438.2 1766.53  5473.1 1766.81
#Mann=8,-1,0
  4241.4   0.035       0  4247.2    0.16       0  4247.3    0.07       0
  4388.8    0.16       0  4658.6    0.07       0  4961.6    0.07       0
  4965.6    0.07       0  5344.2   0.035       0
Bank Sta=4961.6,4965.6
Exp/Cntr=0.3,0.1

Type RM Length L Ch R = 1,5811,221,221,221
BEGIN DESCRIPTION:
Elm 01 43 5810.78
END DESCRIPTION:
XS GIS Cut Line= 3
      1554273.93      6846620.11      1554745.29      6846185.21
      1555164.54      6845716.49
#Sta/Elev= 30
  4356.1 1765.26  4520.8 1762.40  4528.2 1763.08  4535.0 1762.06  4542.4 1763.11
  4563.4 1763.48  4570.7 1761.91  4584.9 1760.99  4634.3 1759.55  4733.5 1758.74
  4754.5 1759.88  4761.8 1758.19  4776.0 1758.15  4811.2 1760.45  4861.0 1758.79
  4874.7 1759.75  4882.1 1758.75  4888.9 1759.66  4896.2 1758.36  4979.3 1757.03
  4979.5 1756.53  4983.3 1757.03  4988.1 1758.04  4997.4 1757.65  5172.2 1757.33
  5271.6 1758.47  5597.4 1764.92  5611.0 1764.44  5618.5 1766.47  5626.3 1766.93
#Mann=4,-1,0
  4356.1    0.07       0  4979.3   0.035       0  4983.3    0.07       0
  4997.4   0.035       0
Bank Sta=4979.3,4983.3
Exp/Cntr=0.3,0.1

Type RM Length L Ch R = 1,5590,206,206,206
BEGIN DESCRIPTION:
Elm 01 43 5589.711
END DESCRIPTION:
XS GIS Cut Line= 3
      1554505.01      6846737.99      1554853.54      6846341.90
      1555305.00      6845738.00
#Sta/Elev= 30
  4472.4 1765.23  4508.0 1764.70  4536.4 1763.13  4543.1 1763.58  4563.8 1762.89
  4700.5 1760.16  4748.9 1758.83  4884.9 1757.10  4939.7 1756.30  4953.9 1755.33
  4982.4 1755.53  4999.3 1754.16  5009.0 1754.11  5009.2 1753.61  5013.0 1754.11
  5025.5 1758.46  5046.4 1755.71  5075.6 1755.38  5081.8 1756.20  5091.5 1755.93
  5125.6 1756.04  5131.8 1755.43  5274.5 1757.41  5467.4 1761.25  5561.2 1762.28
  5704.1 1765.68  5717.5 1766.73  5725.9 1765.70  5732.1 1766.88  5754.0 1767.80
#Mann=8,-1,0
  4472.4    0.07       0  4563.8   0.035       0  4700.5    0.07       0
  4884.9   0.035       0  5009.0   0.035       0  5013.0   0.035       0
  5091.5    0.07       0  5274.5   0.035       0
Bank Sta=5009,5013
Exp/Cntr=0.3,0.1

Type RM Length L Ch R = 1,5384,322,322,322
BEGIN DESCRIPTION:
Elm 01 43 5384.48
END DESCRIPTION:
XS GIS Cut Line= 3
      1554635.88      6846820.66      1554969.25      6846502.92
      1555307.82      6845995.07
#Sta/Elev= 30
  4538.2 1763.92  4645.7 1762.06  4652.6 1762.57  4674.0 1761.16  4840.8 1757.47
  4893.2 1757.15  4907.4 1759.18  4914.3 1757.77  4942.6 1754.42  4970.9 1754.72
  5005.4 1753.56  5035.4 1754.82  5041.4 1755.56  5084.5 1753.19  5084.7 1752.69
  5088.2 1752.69  5088.5 1753.19  5128.6 1753.86  5143.6 1756.34  5149.6 1756.65
  5158.6 1756.48  5172.9 1754.56  5179.6 1755.24  5276.7 1756.53  5353.2 1758.08
  5359.9 1757.61  5402.0 1758.34  5497.4 1760.93  5519.2 1760.90  5609.1 1763.00
#Mann=5,-1,0
  4538.2   0.035       0  4840.8    0.07       0  5084.5    0.07       0
  5088.5    0.07       0  5276.7   0.035       0
Bank Sta=5084.5,5088.5
Exp/Cntr=0.3,0.1

Type RM Length L Ch R = 1,5062,139,139,139
BEGIN DESCRIPTION:
Elm 01 43 5062.12
END DESCRIPTION:
XS GIS Cut Line= 3
      1554805.21      6846909.14      1555190.60      6846426.53
      1555388.53      6846134.86
#Sta/Elev= 30
  4380.0 1762.19  4615.1 1756.69  4719.3 1755.65  4743.2 1756.56  4751.2 1758.62
  4765.4 1758.72  4772.0 1757.55  4786.4 1757.49  4821.7 1758.52  4836.1 1757.41
  4842.5 1758.36  4850.5 1757.32  4856.9 1758.25  4864.9 1757.61  4885.7 1758.59
  4900.1 1757.66  4906.5 1759.16  4914.5 1758.04  4920.9 1758.59  4928.9 1757.73
  4941.8 1758.17  4949.8 1757.66  4957.3 1758.27  4970.6 1754.97  4978.6 1754.37
  5005.9 1754.29  5006.2 1753.79  5009.9 1754.29  5265.7 1759.42  5350.1 1761.91
#Mann=5,-1,0
  4380.0   0.035       0  4719.3    0.07       0  4941.8   0.035       0
  5005.9   0.035       0  5009.9   0.035       0
Bank Sta=5005.9,5009.9
Exp/Cntr=0.3,0.1

Type RM Length L Ch R = 1,4923,209,209,209
BEGIN DESCRIPTION:
Elm 01 43 4922.72
END DESCRIPTION:
XS GIS Cut Line= 3
      1554916.29      6846975.16      1555260.05      6846541.11
      1555509.20      6846201.99
#Sta/Elev= 30
  4445.0 1760.87  4499.0 1759.38  4527.9 1757.48  4563.1 1758.38  4598.4 1757.31
  4606.4 1757.63  4612.8 1756.72  4627.2 1757.36  4633.6 1756.66  4641.7 1756.91
  4648.1 1756.17  4662.5 1755.91  4784.3 1754.77  4798.6 1755.11  4832.0 1754.41
  4874.9 1754.16  4918.9 1753.33  4958.6 1753.39  4966.6 1753.23  4966.8 1752.73
  4970.3 1752.73  4970.6 1753.23  4999.1 1753.32  5062.3 1753.80  5139.5 1756.03
  5162.6 1755.89  5176.3 1757.16  5183.4 1756.32  5235.6 1757.82  5419.5 1762.26
#Mann=8,-1,0
  4445.0   0.035       0  4832.0    0.07       0  4874.9   0.035       0
  4958.6    0.07       0  4966.6   0.035       0  4970.6    0.07       0
  4999.1   0.035       0  5235.6    0.16       0
Bank Sta=4966.6,4970.6
Exp/Cntr=0.3,0.1

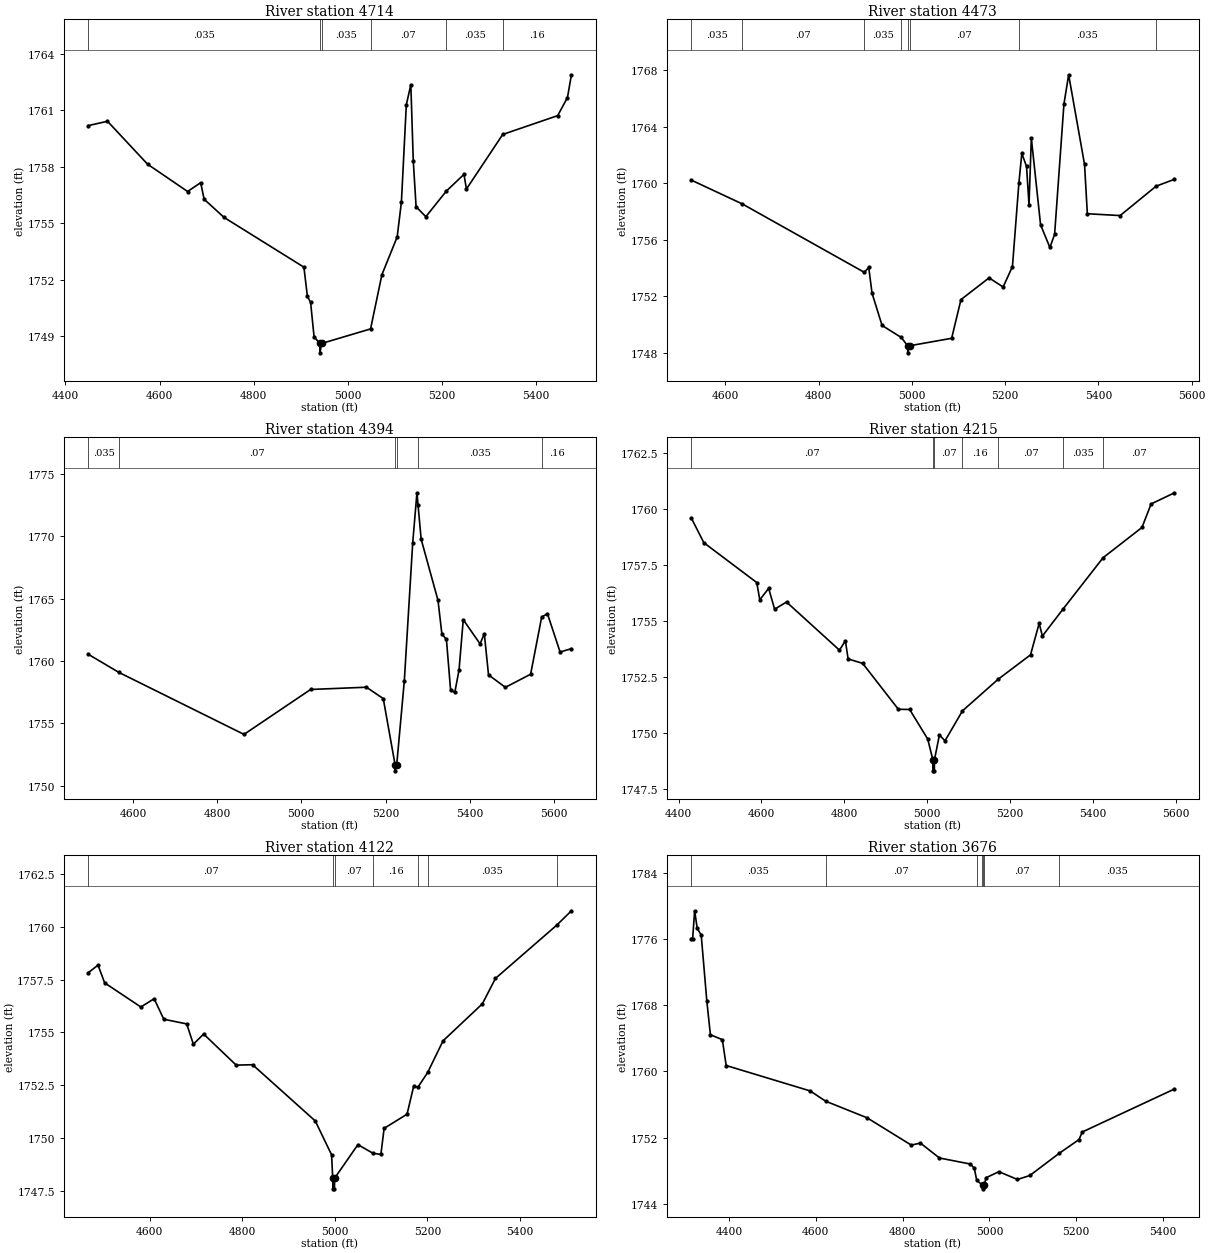
Type RM Length L Ch R = 1,4714,241,241,241
BEGIN DESCRIPTION:
Elm 01 43 4814.13
END DESCRIPTION:
XS GIS Cut Line= 3
      1554968.37      6847079.32      1555402.35      6846683.74
      1555520.46      6846259.90
#Sta/Elev= 30
  4448.4 1760.18  4489.3 1760.41  4574.5 1758.13  4659.6 1756.68  4687.4 1757.15
  4694.7 1756.27  4737.3 1755.30  4906.9 1752.66  4914.3 1751.11  4921.1 1750.79
  4928.5 1748.96  4940.7 1748.61  4940.9 1748.11  4944.7 1748.61  5048.6 1749.38
  5072.7 1752.26  5105.2 1754.27  5114.2 1756.13  5124.6 1761.28  5134.2 1762.36
  5139.4 1758.30  5145.4 1755.87  5166.1 1755.34  5209.6 1756.70  5247.2 1757.59
  5252.4 1756.81  5329.6 1759.71  5446.4 1760.71  5467.2 1761.67  5475.6 1762.88
#Mann=6,-1,0
  4448.4   0.035       0  4940.7   0.035       0  4944.7   0.035       0
  5048.6    0.07       0  5209.6   0.035       0  5329.6    0.16       0
Bank Sta=4940.7,4944.7
Exp/Cntr=0.3,0.1

Type RM Length L Ch R = 1,4473,79,79,79
BEGIN DESCRIPTION:
Elm 01 43 4568.98
END DESCRIPTION:
XS GIS Cut Line= 3
      1555058.49      6847207.56      1555463.41      6846866.93
      1555506.47      6846361.80
#Sta/Elev= 30
  4527.1 1760.21  4636.6 1758.52  4898.1 1753.68  4907.5 1754.03  4914.6 1752.20
  4936.1 1749.92  4977.2 1749.07  4991.0 1748.48  4991.2 1747.98  4995.0 1748.48
  5085.3 1749.01  5105.3 1751.75  5165.6 1753.29  5195.7 1752.64  5215.7 1754.09
  5229.5 1760.00  5235.8 1762.10  5245.9 1761.18  5251.2 1758.46  5256.2 1763.18
  5276.0 1757.05  5296.0 1755.44  5306.1 1756.37  5326.1 1765.59  5336.2 1767.67
  5370.3 1761.32  5376.3 1757.83  5446.6 1757.70  5523.7 1759.78  5563.2 1760.27
#Mann=8,-1,0
  4527.1   0.035       0  4636.6    0.07       0  4898.1   0.035       0
  4977.2    0.07       0  4991.0    0.07       0  4995.0    0.07       0
  5229.5   0.035       0  5523.7    0.16       0
Bank Sta=4991,4995
Exp/Cntr=0.3,0.1

Type RM Length L Ch R = 1,4394,179,179,179
BEGIN DESCRIPTION:
Elm 01 43 4394.21
END DESCRIPTION:
XS GIS Cut Line= 4
      1555065.62      6847256.38      1555496.16      6846943.89
      1555516.99      6846867.50      1555523.91      6846331.12
#Sta/Elev= 30
  4493.9 1760.54  4566.5 1759.09  4863.8 1754.12  5022.1 1757.72  5154.6 1757.90
  5194.6 1756.99  5222.6 1751.70  5222.8 1751.20  5226.6 1751.70  5244.6 1758.40
  5264.6 1769.49  5274.6 1773.48  5277.2 1772.51  5284.6 1769.76  5324.6 1764.86
  5333.9 1762.15  5344.6 1761.74  5354.6 1757.64  5364.6 1757.50  5374.6 1759.29
  5384.6 1763.31  5424.6 1761.37  5434.6 1762.19  5444.6 1758.89  5484.6 1757.89
  5544.6 1758.94  5570.9 1763.53  5584.6 1763.79  5614.6 1760.72  5641.5 1760.99
#Mann=6,-1,0
  4493.9   0.035       0  4566.5    0.07       0  5222.6    0.07       0
  5226.6    0.07       0  5277.2   0.035       0  5570.9    0.16       0
Bank Sta=5222.6,5226.6
Exp/Cntr=0.3,0.1

Type RM Length L Ch R = 1,4215,93,93,93
BEGIN DESCRIPTION:
Elm 01 43 4215.88
END DESCRIPTION:
XS GIS Cut Line= 3
      1555187.10      6847322.39      1555617.06      6846971.02
      1556013.54      6846506.36
#Sta/Elev= 30
  4430.8 1759.58  4460.9 1758.48  4588.7 1756.70  4596.0 1755.93  4617.4 1756.44
  4631.8 1755.51  4660.5 1755.83  4788.3 1753.68  4802.6 1754.10  4809.1 1753.29
  4844.3 1753.09  4930.4 1751.04  4957.7 1751.03  5001.3 1749.71  5013.6 1748.79
  5013.8 1748.29  5017.3 1748.29  5017.6 1748.79  5029.5 1749.89  5043.0 1749.63
  5085.2 1750.97  5171.2 1752.38  5249.4 1753.47  5270.3 1754.88  5278.0 1754.31
  5328.9 1755.54  5424.6 1757.81  5518.4 1759.16  5540.4 1760.21  5596.9 1760.71
#Mann=7,-1,0
  4430.8    0.07       0  5013.6    0.07       0  5017.6    0.07       0
  5085.2    0.16       0  5171.2    0.07       0  5328.9   0.035       0
  5424.6    0.07       0
Bank Sta=5013.6,5017.6
Exp/Cntr=0.3,0.1

Type RM Length L Ch R = 1,4122,446,446,446
BEGIN DESCRIPTION:
Elm 01 43 4122.06
END DESCRIPTION:
XS GIS Cut Line= 3
      1555280.87      6847364.04      1555690.60      6847027.23
      1556055.15      6846666.15
#Sta/Elev= 30
  4467.6 1757.82  4488.7 1758.18  4503.0 1757.34  4581.2 1756.20  4609.9 1756.59
  4630.7 1755.62  4680.2 1755.40  4694.6 1754.44  4716.8 1754.92  4787.1 1753.45
  4822.5 1753.47  4957.9 1750.81  4993.1 1749.21  4995.6 1748.10  4995.9 1747.60
  4999.4 1747.60  4999.6 1748.10  5050.0 1749.69  5082.7 1749.28  5099.6 1749.23
  5106.6 1750.46  5156.1 1751.13  5170.3 1752.44  5179.7 1752.41  5200.8 1753.11
  5233.9 1754.60  5318.8 1756.35  5347.0 1757.55  5479.4 1760.07  5511.1 1760.75
#Mann=7,-1,0
  4467.6    0.07       0  4995.6    0.07       0  4999.6    0.07       0
  5082.7    0.16       0  5179.7    0.07       0  5200.8   0.035       0
  5479.4    0.07       0
Bank Sta=4995.6,4999.6
Exp/Cntr=0.3,0.1

Type RM Length L Ch R = 1,3676,336,336,336
BEGIN DESCRIPTION:
Elm 01 43 3675.696
END DESCRIPTION:
XS GIS Cut Line= 3
      1555305.01      6847738.00      1555881.72      6847365.60
      1556204.99      6847088.01
#Sta/Elev= 30
  4313.5 1776.04  4316.5 1776.04  4321.1 1779.39  4327.0 1777.27  4336.2 1776.47
  4349.2 1768.46  4357.4 1764.43  4384.9 1763.84  4393.7 1760.72  4587.3 1757.65
  4622.6 1756.42  4718.2 1754.41  4819.9 1751.12  4841.0 1751.36  4884.9 1749.56
  4956.3 1748.83  4965.1 1748.32  4970.7 1746.86  4982.2 1746.36  4984.2 1746.34
  4984.5 1745.84  4988.2 1746.34  4992.2 1747.18  5021.7 1747.91  5064.5 1746.97
  5093.0 1747.45  5161.0 1750.14  5206.1 1751.78  5213.8 1752.70  5426.1 1757.89
#Mann=7,-1,0
  4313.5   0.035       0  4622.6    0.07       0  4970.7   0.035       0
  4982.2    0.07       0  4984.2    0.07       0  4988.2    0.07       0
  5161.0   0.035       0
Bank Sta=4984.2,4988.2
Exp/Cntr=0.3,0.1

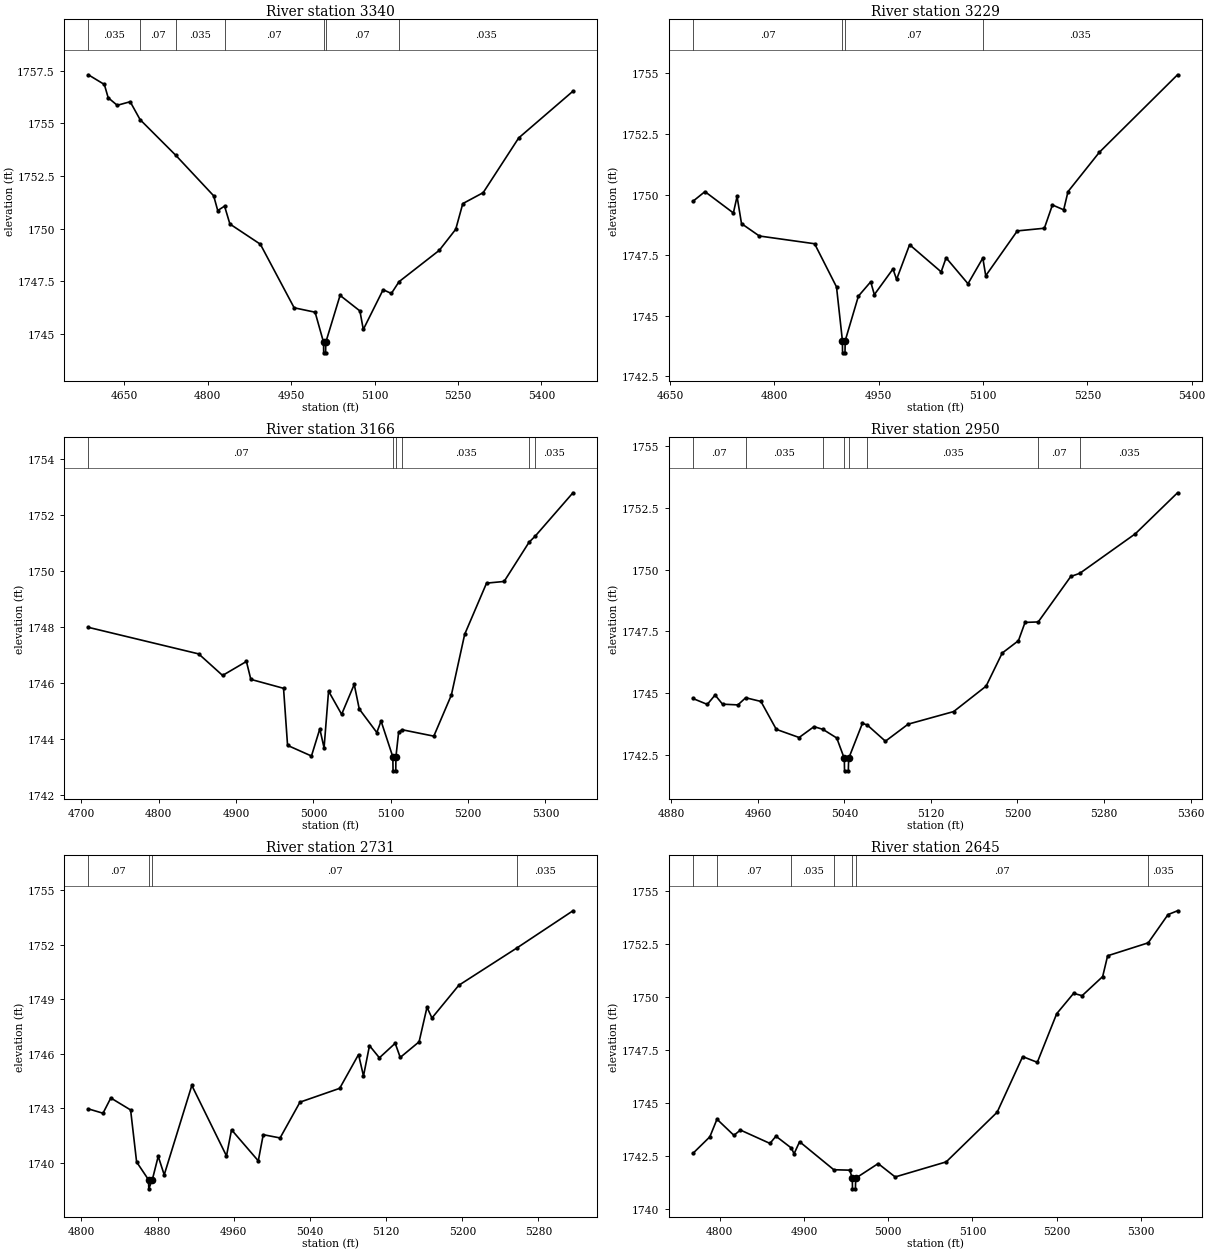
Type RM Length L Ch R = 1,3340,111,111,111
BEGIN DESCRIPTION:
Elm 01 43 3340.38
END DESCRIPTION:
XS GIS Cut Line= 3
      1555652.40      6847784.18      1556041.30      6847610.56
      1556298.23      6847246.00
#Sta/Elev= 30
  4585.0 1757.31  4613.8 1756.85  4620.7 1756.22  4637.0 1755.86  4660.3 1756.03
  4678.1 1755.18  4742.5 1753.48  4810.5 1751.56  4817.8 1750.86  4830.1 1751.07
  4839.7 1750.22  4894.5 1749.26  4955.3 1746.24  4993.0 1746.03  5008.2 1744.60
  5008.4 1744.10  5011.9 1744.10  5012.2 1744.60  5037.9 1746.83  5073.6 1746.09
  5079.7 1745.21  5115.4 1747.10  5130.2 1746.92  5144.0 1747.48  5216.4 1748.97
  5246.0 1749.97  5258.7 1751.19  5295.4 1751.71  5359.3 1754.31  5456.9 1756.53
#Mann=7,-1,0
  4585.0   0.035       0  4678.1    0.07       0  4742.5   0.035       0
  4830.1    0.07       0  5008.2    0.07       0  5012.2    0.07       0
  5144.0   0.035       0
Bank Sta=5008.2,5012.2
Exp/Cntr=0.3,0.1

Type RM Length L Ch R = 1,3229,63,63,63
BEGIN DESCRIPTION:
Elm 01 43 3189.489
END DESCRIPTION:
XS GIS Cut Line= 3
      1556030.85      6847964.49      1556162.42      6847557.12
      1556284.85      6847317.81
#Sta/Elev= 30
  4682.7 1749.72  4700.0 1750.12  4740.9 1749.24  4746.2 1749.92  4752.6 1748.80
  4778.2 1748.29  4857.7 1747.97  4889.2 1746.19  4897.7 1743.97  4897.9 1743.47
  4901.4 1743.47  4901.7 1743.97  4920.7 1745.81  4938.4 1746.40  4943.6 1745.87
  4970.4 1746.93  4975.6 1746.50  4994.3 1747.93  5039.7 1746.81  5046.8 1747.39
  5078.3 1746.32  5099.6 1747.38  5103.8 1746.65  5149.2 1748.50  5188.1 1748.61
  5199.7 1749.57  5215.9 1749.37  5222.1 1750.12  5267.1 1751.74  5379.6 1754.94
#Mann=4,-1,0
  4682.7    0.07       0  4897.7    0.07       0  4901.7    0.07       0
  5099.6   0.035       0
Bank Sta=4897.7,4901.7
Exp/Cntr=0.3,0.1

Type RM Length L Ch R = 1,3166,216,216,216
BEGIN DESCRIPTION:
Elm 01 43 3.0
END DESCRIPTION:
XS GIS Cut Line= 3
      1556101.62      6847986.91      1556161.82      6847731.73
      1556318.17      6847402.57
#Sta/Elev= 30
  4709.0 1747.99  4851.7 1747.04  4882.6 1746.27  4913.4 1746.77  4919.1 1746.13
  4961.4 1745.81  4966.6 1743.77  4997.5 1743.39  5008.3 1744.36  5013.8 1743.68
  5019.6 1745.71  5036.5 1744.88  5052.8 1745.95  5059.3 1745.07  5082.0 1744.23
  5087.5 1744.64  5102.7 1743.36  5103.0 1742.86  5106.5 1742.86  5106.7 1743.36
  5110.2 1744.24  5114.6 1744.33  5155.7 1744.10  5178.4 1745.57  5195.6 1747.74
  5223.9 1749.57  5246.6 1749.63  5278.8 1751.03  5286.8 1751.25  5335.6 1752.80
#Mann=6,-1,0
  4709.0    0.07       0  5102.7    0.07       0  5106.7    0.07       0
  5114.6   0.035       0  5278.8    0.07       0  5286.8   0.035       0
Bank Sta=5102.7,5106.7
Exp/Cntr=0.3,0.1

Type RM Length L Ch R = 1,2950,219,219,219
BEGIN DESCRIPTION:
Elm 01 43 2951.36
END DESCRIPTION:
XS GIS Cut Line= 3
      1556294.53      6847856.42      1556367.69      6847780.70
      1556558.65      6847496.00
#Sta/Elev= 30
  4899.9 1744.78  4913.2 1744.54  4920.4 1744.92  4927.3 1744.55  4941.5 1744.52
  4948.7 1744.81  4962.8 1744.66  4977.0 1743.53  4998.1 1743.20  5011.9 1743.64
  5020.1 1743.53  5032.9 1743.18  5039.9 1742.35  5040.1 1741.85  5043.6 1741.85
  5043.9 1742.35  5056.6 1743.77  5061.0 1743.71  5077.9 1743.05  5098.9 1743.74
  5141.0 1744.25  5171.0 1745.28  5185.9 1746.62  5200.9 1747.12  5207.0 1747.86
  5219.2 1747.88  5249.3 1749.72  5257.7 1749.85  5309.0 1751.45  5348.0 1753.11
#Mann=8,-1,0
  4899.9    0.07       0  4948.7   0.035       0  5020.1    0.07       0
  5039.9   0.035       0  5043.9    0.07       0  5061.0   0.035       0
  5219.2    0.07       0  5257.7   0.035       0
Bank Sta=5039.9,5043.9
Exp/Cntr=0.3,0.1

Type RM Length L Ch R = 1,2731,86,86,86
BEGIN DESCRIPTION:
Elm 01 43 2.0
END DESCRIPTION:
XS GIS Cut Line= 3
      1556452.33      6847957.50      1556538.34      6847846.66
      1556642.38      6847492.94
#Sta/Elev= 30
  4807.2 1742.97  4822.6 1742.73  4830.8 1743.57  4851.6 1742.91  4857.9 1740.05
  4870.4 1739.07  4870.7 1738.57  4874.4 1739.07  4880.6 1740.36  4886.9 1739.34
  4915.9 1744.26  4952.3 1740.38  4957.6 1741.82  4985.7 1740.11  4990.9 1741.55
  5008.6 1741.37  5029.5 1743.34  5071.2 1744.10  5091.0 1745.96  5096.2 1744.78
  5102.5 1746.45  5112.9 1745.78  5129.5 1746.58  5134.8 1745.80  5154.6 1746.66
  5162.9 1748.56  5168.1 1747.97  5196.3 1749.77  5257.5 1751.83  5316.2 1753.87
#Mann=4,-1,0
  4807.2    0.07       0  4870.4    0.07       0  4874.4    0.07       0
  5257.5   0.035       0
Bank Sta=4870.4,4874.4
Exp/Cntr=0.3,0.1

Type RM Length L Ch R = 1,2645,212,212,212
BEGIN DESCRIPTION:
Elm 01 43 2670.17
END DESCRIPTION:
XS GIS Cut Line= 3
      1556521.00      6848033.09      1556614.06      6847923.85
      1556672.06      6847495.76
#Sta/Elev= 30
  4768.1 1742.64  4788.2 1743.42  4796.7 1744.25  4816.8 1743.49  4824.5 1743.74
  4859.6 1743.11  4866.7 1743.45  4885.1 1742.89  4888.2 1742.62  4894.8 1743.19
  4935.4 1741.87  4954.3 1741.85  4957.4 1741.47  4957.6 1740.97  4961.1 1740.97
  4961.4 1741.47  4988.1 1742.16  5008.3 1741.53  5068.9 1742.24  5129.4 1744.58
  5159.7 1747.20  5177.1 1746.93  5200.1 1749.22  5220.2 1750.18  5230.3 1750.07
  5254.7 1750.97  5260.6 1751.95  5308.8 1752.56  5332.3 1753.89  5343.6 1754.07
#Mann=7,-1,0
  4768.1    0.16       0  4796.7    0.07       0  4885.1   0.035       0
  4935.4    0.07       0  4957.4    0.07       0  4961.4    0.07       0
  5308.8   0.035       0
Bank Sta=4957.4,4961.4
Exp/Cntr=0.3,0.1

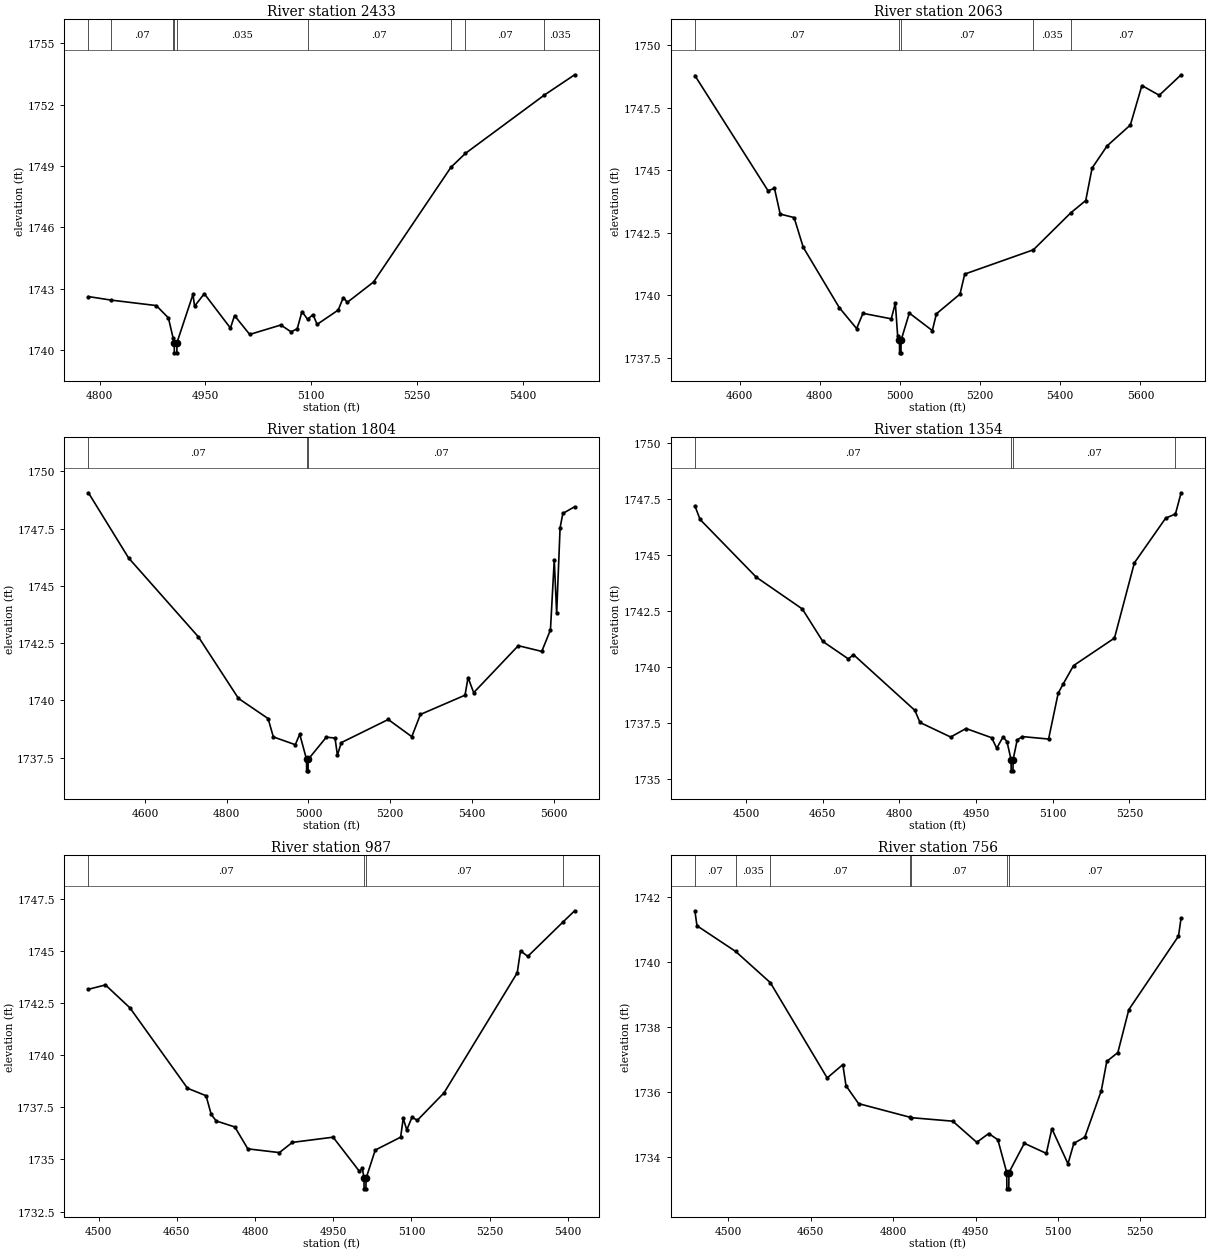
Type RM Length L Ch R = 1,2433,370,370,370
BEGIN DESCRIPTION:
Elm 01 43 2433.12
END DESCRIPTION:
XS GIS Cut Line= 3
      1556573.58      6848070.70      1556722.72      6848042.20
      1556996.18      6847579.28
#Sta/Elev= 30
  4784.2 1742.62  4815.8 1742.45  4880.4 1742.18  4897.6 1741.58  4904.2 1740.61
  4905.8 1740.37  4906.1 1739.87  4909.6 1739.87  4909.8 1740.37  4932.5 1742.73
  4934.7 1742.15  4948.5 1742.76  4985.6 1741.08  4991.4 1741.69  5012.9 1740.77
  5057.1 1741.23  5071.4 1740.90  5080.3 1741.04  5087.0 1741.89  5095.0 1741.51
  5102.7 1741.74  5108.5 1741.26  5138.4 1741.96  5145.6 1742.57  5151.4 1742.34
  5188.5 1743.33  5298.3 1748.94  5318.9 1749.62  5430.8 1752.47  5473.7 1753.46
#Mann=9,-1,0
  4784.2    0.16       0  4815.8    0.07       0  4904.2   0.035       0
  4905.8   0.035       0  4909.8   0.035       0  5095.0    0.07       0
  5298.3   0.035       0  5318.9    0.07       0  5430.8   0.035       0
Bank Sta=4905.8,4909.8
Exp/Cntr=0.3,0.1

Type RM Length L Ch R = 1,2063,259,259,259
BEGIN DESCRIPTION:
Elm 01 43 2063.27
END DESCRIPTION:
XS GIS Cut Line= 3
      1556339.89      6848572.37      1556780.88      6848322.36
      1557128.10      6847707.79
#Sta/Elev= 30
  4488.5 1748.78  4671.1 1744.17  4687.0 1744.27  4701.3 1743.24  4736.0 1743.10
  4758.8 1741.91  4848.6 1739.50  4891.9 1738.66  4907.7 1739.27  4978.4 1739.05
  4988.5 1739.68  4994.3 1738.36  4998.8 1738.19  4999.1 1737.69  5002.6 1737.69
  5002.8 1738.19  5023.4 1739.28  5080.8 1738.58  5090.9 1739.25  5149.8 1740.04
  5161.6 1740.84  5332.8 1741.81  5426.2 1743.29  5463.4 1743.78  5479.3 1745.08
  5516.9 1745.97  5574.7 1746.80  5603.5 1748.38  5646.8 1747.99  5701.3 1748.81
#Mann=5,-1,0
  4488.5    0.07       0  4998.8    0.07       0  5002.8    0.07       0
  5332.8   0.035       0  5426.2    0.07       0
Bank Sta=4998.8,5002.8
Exp/Cntr=0.3,0.1

Type RM Length L Ch R = 1,1804,450,450,450
BEGIN DESCRIPTION:
Elm 01 43 1803.783
END DESCRIPTION:
XS GIS Cut Line= 3
      1556454.97      6848688.01      1556954.65      6848487.52
      1557305.00      6847938.00
#Sta/Elev= 30
  4461.6 1749.06  4559.8 1746.22  4731.0 1742.77  4828.8 1740.09  4901.4 1739.21
  4914.2 1738.41  4968.0 1738.07  4978.8 1738.53  4995.5 1737.43  4995.7 1736.93
  4999.2 1736.93  4999.5 1737.43  5044.0 1738.40  5065.2 1738.36  5071.1 1737.61
  5080.4 1738.16  5195.5 1739.17  5253.1 1738.42  5274.2 1739.39  5383.4 1740.23
  5390.8 1741.00  5404.6 1740.34  5513.8 1742.39  5571.3 1742.14  5592.5 1743.08
  5601.8 1746.13  5607.7 1743.80  5616.1 1747.54  5622.9 1748.16  5651.7 1748.45
#Mann=3,-1,0
  4461.6    0.07       0  4995.5    0.07       0  4999.5    0.07       0
Bank Sta=4995.5,4999.5
Exp/Cntr=0.3,0.1

Type RM Length L Ch R = 1,1354,367,367,367
BEGIN DESCRIPTION:
Elm 01 43 1354.011
END DESCRIPTION:
XS GIS Cut Line= 3
      1556554.95      6848688.00      1557154.42      6848708.04
      1557505.05      6848688.00
#Sta/Elev= 30
  4400.2 1747.20  4410.3 1746.59  4520.3 1744.01  4610.4 1742.59  4650.4 1741.14
  4700.4 1740.36  4710.4 1740.55  4830.5 1738.06  4840.5 1737.52  4900.5 1736.87
  4930.5 1737.25  4980.6 1736.84  4990.6 1736.37  5002.8 1736.87  5010.6 1736.67
  5018.6 1735.86  5018.9 1735.36  5022.4 1735.36  5022.6 1735.86  5030.6 1736.74
  5040.6 1736.89  5092.0 1736.78  5110.8 1738.83  5120.8 1739.25  5140.8 1740.06
  5220.9 1741.29  5259.8 1744.65  5321.1 1746.65  5340.1 1746.83  5351.2 1747.78
#Mann=4,-1,0
  4400.2    0.07       0  5018.6    0.07       0  5022.6    0.07       0
  5340.1   0.045       0
Bank Sta=5018.6,5022.6
Exp/Cntr=0.3,0.1

Type RM Length L Ch R = 1,987,231,231,231
BEGIN DESCRIPTION:
Elm 01 43 917.487
END DESCRIPTION:
XS GIS Cut Line= 3
      1556664.49      6848895.46      1557085.19      6849053.11
      1557564.12      6848989.50
#Sta/Elev= 30
  4480.5 1743.17  4513.1 1743.38  4560.1 1742.28  4670.5 1738.42  4706.1 1738.06
  4716.0 1737.16  4725.6 1736.85  4761.3 1736.56  4786.2 1735.51  4846.7 1735.33
  4871.6 1735.82  4949.7 1736.07  5000.2 1734.43  5005.9 1734.58  5008.9 1734.09
  5009.2 1733.59  5012.7 1733.59  5012.9 1734.09  5030.5 1735.45  5079.2 1736.07
  5084.2 1736.97  5091.0 1736.42  5101.1 1737.03  5111.2 1736.88  5162.5 1738.20
  5302.8 1743.96  5309.1 1745.02  5323.0 1744.75  5390.1 1746.39  5412.9 1746.94
#Mann=4,-1,0
  4480.5    0.07       0  5008.9    0.07       0  5012.9    0.07       0
  5390.1   0.045       0
Bank Sta=5008.9,5012.9
Exp/Cntr=0.3,0.1

Type RM Length L Ch R = 1,756,176,176,176
BEGIN DESCRIPTION:
Elm 01 43 755.63
END DESCRIPTION:
XS GIS Cut Line= 3
      1556614.23      6848992.51      1557096.85      6849259.86
      1557430.08      6849242.51
#Sta/Elev= 30
  4438.9 1741.58  4442.7 1741.12  4513.1 1740.33  4576.3 1739.37  4679.8 1736.44
  4708.3 1736.85  4714.1 1736.20  4737.0 1735.65  4830.9 1735.23  4831.7 1735.22
  4908.5 1735.11  4952.2 1734.46  4973.9 1734.73  4990.6 1734.54  5006.8 1733.53
  5007.0 1733.03  5010.5 1733.03  5010.8 1733.53  5038.8 1734.43  5078.9 1734.12
  5088.9 1734.88  5118.3 1733.80  5129.0 1734.43  5149.0 1734.62  5179.0 1736.05
  5189.0 1736.95  5209.1 1737.22  5229.1 1738.54  5319.5 1740.80  5324.3 1741.36
#Mann=7,-1,0
  4438.9    0.07       0  4513.1   0.035       0  4576.3    0.07       0
  4830.9   0.035       0  4831.7    0.07       0  5006.8    0.07       0
  5010.8    0.07       0
Bank Sta=5006.8,5010.8
Exp/Cntr=0.3,0.1

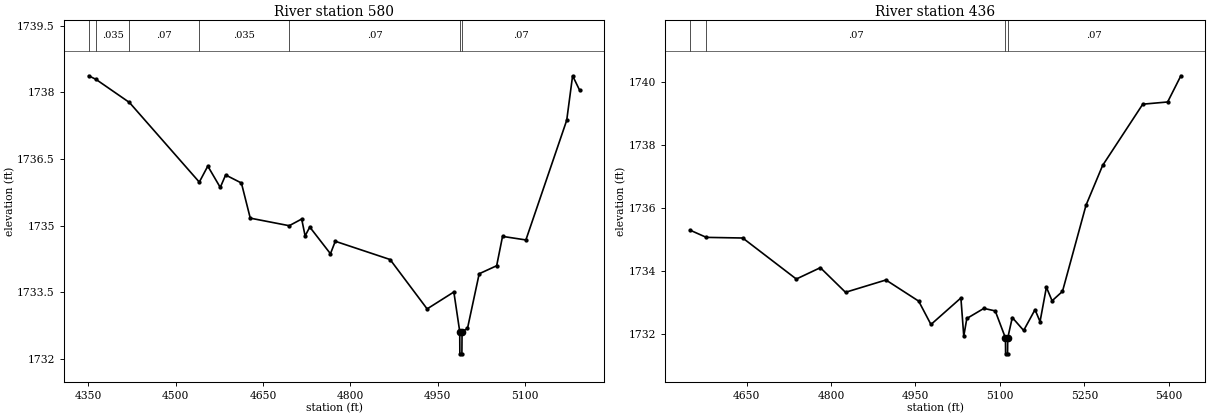
Type RM Length L Ch R = 1,580,144,144,144
BEGIN DESCRIPTION:
Elm 01 43 579.97
END DESCRIPTION:
XS GIS Cut Line= 3
      1556603.82      6849075.85      1557148.94      6849419.59
      1557346.90      6849405.69
#Sta/Elev= 30
  4350.4 1738.37  4362.9 1738.29  4420.4 1737.77  4540.4 1735.98  4555.0 1736.34
  4576.4 1735.86  4585.6 1736.14  4612.7 1735.96  4627.9 1735.17  4694.8 1735.00
  4716.2 1735.15  4722.1 1734.77  4730.1 1734.97  4765.6 1734.37  4773.9 1734.65
  4868.0 1734.24  4931.6 1733.13  4977.5 1733.51  4987.6 1732.62  4987.8 1732.12
  4991.3 1732.12  4991.6 1732.62  5000.9 1732.69  5021.0 1733.92  5051.0 1734.10
  5061.1 1734.76  5101.2 1734.68  5171.3 1737.37  5181.4 1738.37  5193.3 1738.05
#Mann=7,-1,0
  4350.4    0.07       0  4362.9   0.035       0  4420.4    0.07       0
  4540.4   0.035       0  4694.8    0.07       0  4987.6    0.07       0
  4991.6    0.07       0
Bank Sta=4987.6,4991.6
Exp/Cntr=0.3,0.1

Type RM Length L Ch R = 1,436,0,0,0
BEGIN DESCRIPTION:
Elm 01 43 435.538
END DESCRIPTION:
XS GIS Cut Line= 4
      1556718.38      6849315.42      1557104.27      6849548.07
      1557305.52      6849518.95      1557483.02      6849392.12
#Sta/Elev= 30
  4549.4 1735.30  4578.4 1735.07  4643.1 1735.05  4738.3 1733.75  4781.0 1734.11
  4825.7 1733.33  4897.5 1733.72  4955.7 1733.05  4977.5 1732.31  5030.7 1733.15
  5035.8 1731.94  5041.2 1732.50  5071.5 1732.82  5091.7 1732.74  5109.9 1731.88
  5110.1 1731.38  5113.6 1731.38  5113.9 1731.88  5122.0 1732.53  5142.2 1732.12
  5162.4 1732.78  5171.3 1732.40  5182.6 1733.49  5192.7 1733.06  5211.2 1733.36
  5253.0 1736.09  5282.5 1737.35  5353.8 1739.29  5398.0 1739.36  5421.5 1740.19
#Mann=4,-1,0
  4549.4   0.035       0  4578.4    0.07       0  5109.9    0.07       0
  5113.9    0.07       0
Bank Sta=5109.9,5113.9
Exp/Cntr=0.3,0.1

Chan Stop Cuts=-1