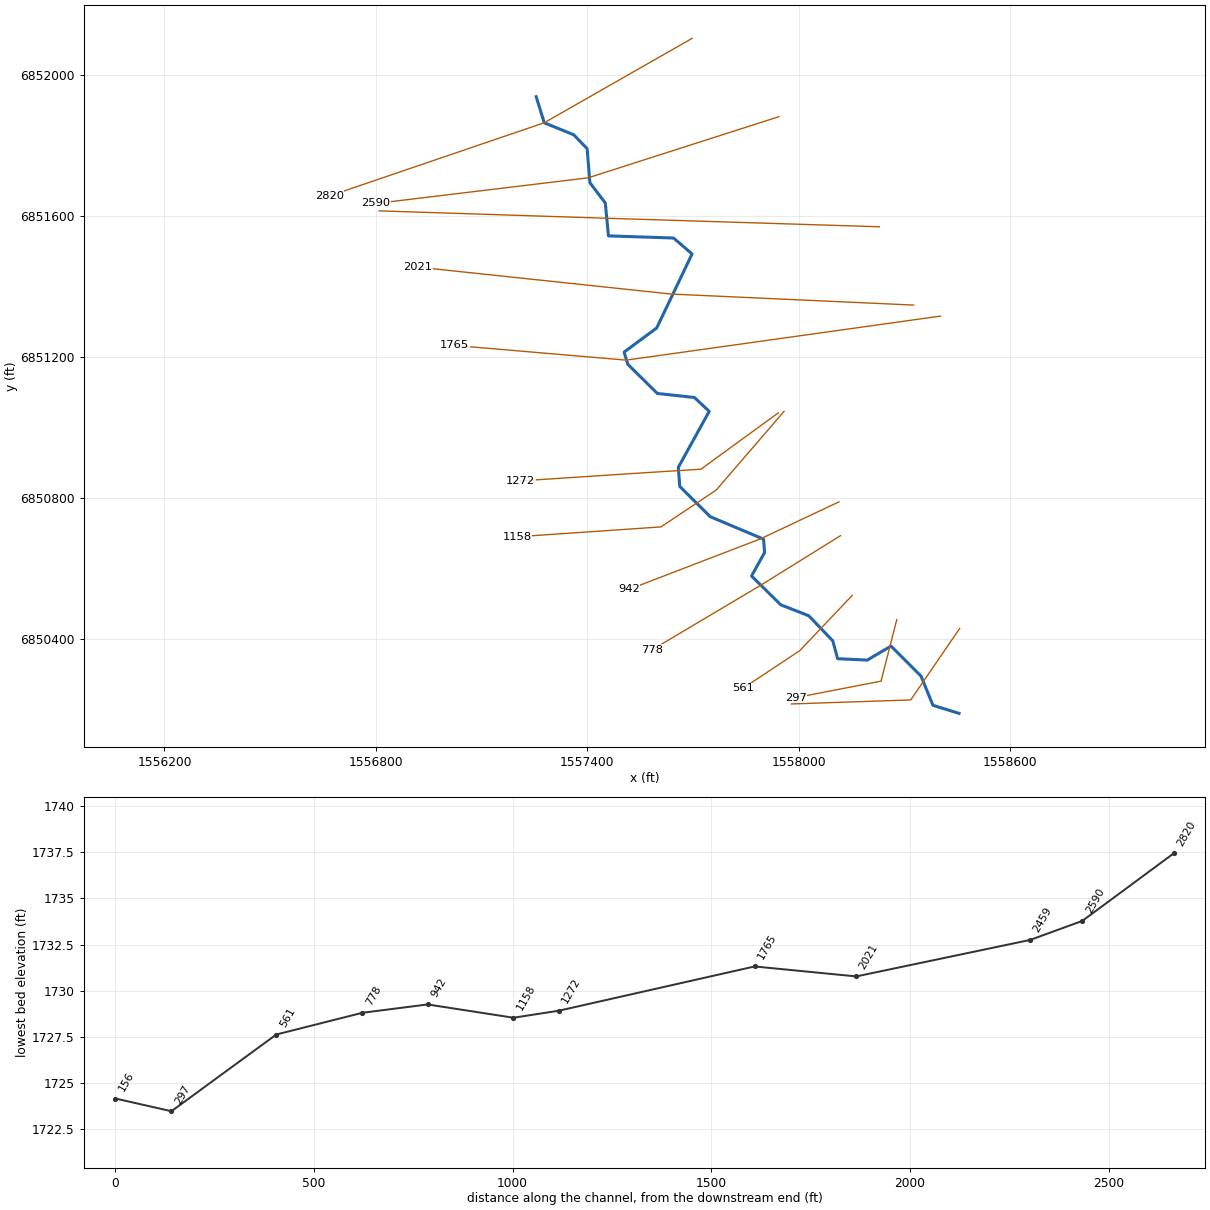
--- Elm 01 44.prj (project) ---

Proj Title=Elm 01 44 Base Level Engineering
Current Plan=p01
Default Exp/Contr=0.3,0.1
English Units
Geom File=g01
Flow File=f01
Plan File=p01
BEGIN DESCRIPTION:
Elm 01 44
END DESCRIPTION:

--- Elm 01 44.p01 (plan) ---

Plan Title=Multiple Run
Short Identifier=Multiple
Geom File=g01
Flow File=f01
Subcritical Flow
K Sum by GR= 0
Std Step Tol= 0.01
Critical Tol= 0.01
Num of Std Step Trials= 20
Max Error Tol= 0.3
Flow Tol Ratio= 0.001
Split Flow NTrial= 30
Split Flow Tol= 0.02
Split Flow Ratio= 0.02
Log Output Level= 0
Friction Slope Method= 1
Unsteady Friction Slope Method= 2
Unsteady Bridges Friction Slope Method= 1
Parabolic Critical Depth
Global Vel Dist=  1 , 1 , 1
Global Log Level= 0
CheckData=True
Encroach Param= -1, 0, 0, 0
BEGIN DESCRIPTION:
Multiple Run
END DESCRIPTION:

--- Elm 01 44.f01 (steady flow) ---

Flow Title=Multiple
Number of Profiles=7
Profile Names=10-year,25-year,50-year,1pct_min,100-year,1pct_plu,500-year
River Rch & RM= Elm 01 44,Reach-1,2820
      72      92     106      77     123     169     166
Boundary for River Rch & Prof#=Elm 01 44,Reach-1,1
Up Type=0
Dn Type=3
Dn Slope=0.005
Boundary for River Rch & Prof#=Elm 01 44,Reach-1,2
Up Type=0
Dn Type=3
Dn Slope=0.005
Boundary for River Rch & Prof#=Elm 01 44,Reach-1,3
Up Type=0
Dn Type=3
Dn Slope=0.005
Boundary for River Rch & Prof#=Elm 01 44,Reach-1,4
Up Type=0
Dn Type=3
Dn Slope=0.005
Boundary for River Rch & Prof#=Elm 01 44,Reach-1,5
Up Type=0
Dn Type=3
Dn Slope=0.005
Boundary for River Rch & Prof#=Elm 01 44,Reach-1,6
Up Type=0
Dn Type=3
Dn Slope=0.005
Boundary for River Rch & Prof#=Elm 01 44,Reach-1,7
Up Type=0
Dn Type=3
Dn Slope=0.005

--- Elm 01 44.g01 (geometry) ---

Geom Title=Existing Conditions

River Reach=Elm 01 44,Reach-1
Reach XY= 30
      1557255.00      6851938.00      1557277.83      6851864.02
      1557361.37      6851829.99      1557399.58      6851790.67
      1557407.36      6851693.98      1557451.11      6851636.32
      1557460.08      6851543.03      1557644.90      6851536.95
      1557697.35      6851491.70      1557596.92      6851281.68
      1557504.38      6851213.08      1557515.06      6851178.56
      1557598.81      6851095.86      1557703.98      6851084.39
      1557746.03      6851045.06      1557658.31      6850886.26
      1557662.47      6850831.93      1557748.93      6850746.13
      1557900.21      6850682.41      1557903.17      6850644.43
      1557866.11      6850577.94      1557948.92      6850496.16
      1558028.51      6850465.00      1558096.70      6850393.71
      1558110.47      6850343.11      1558194.41      6850339.23
      1558261.75      6850378.88      1558346.85      6850294.08
      1558381.02      6850210.82      1558455.00      6850188.00

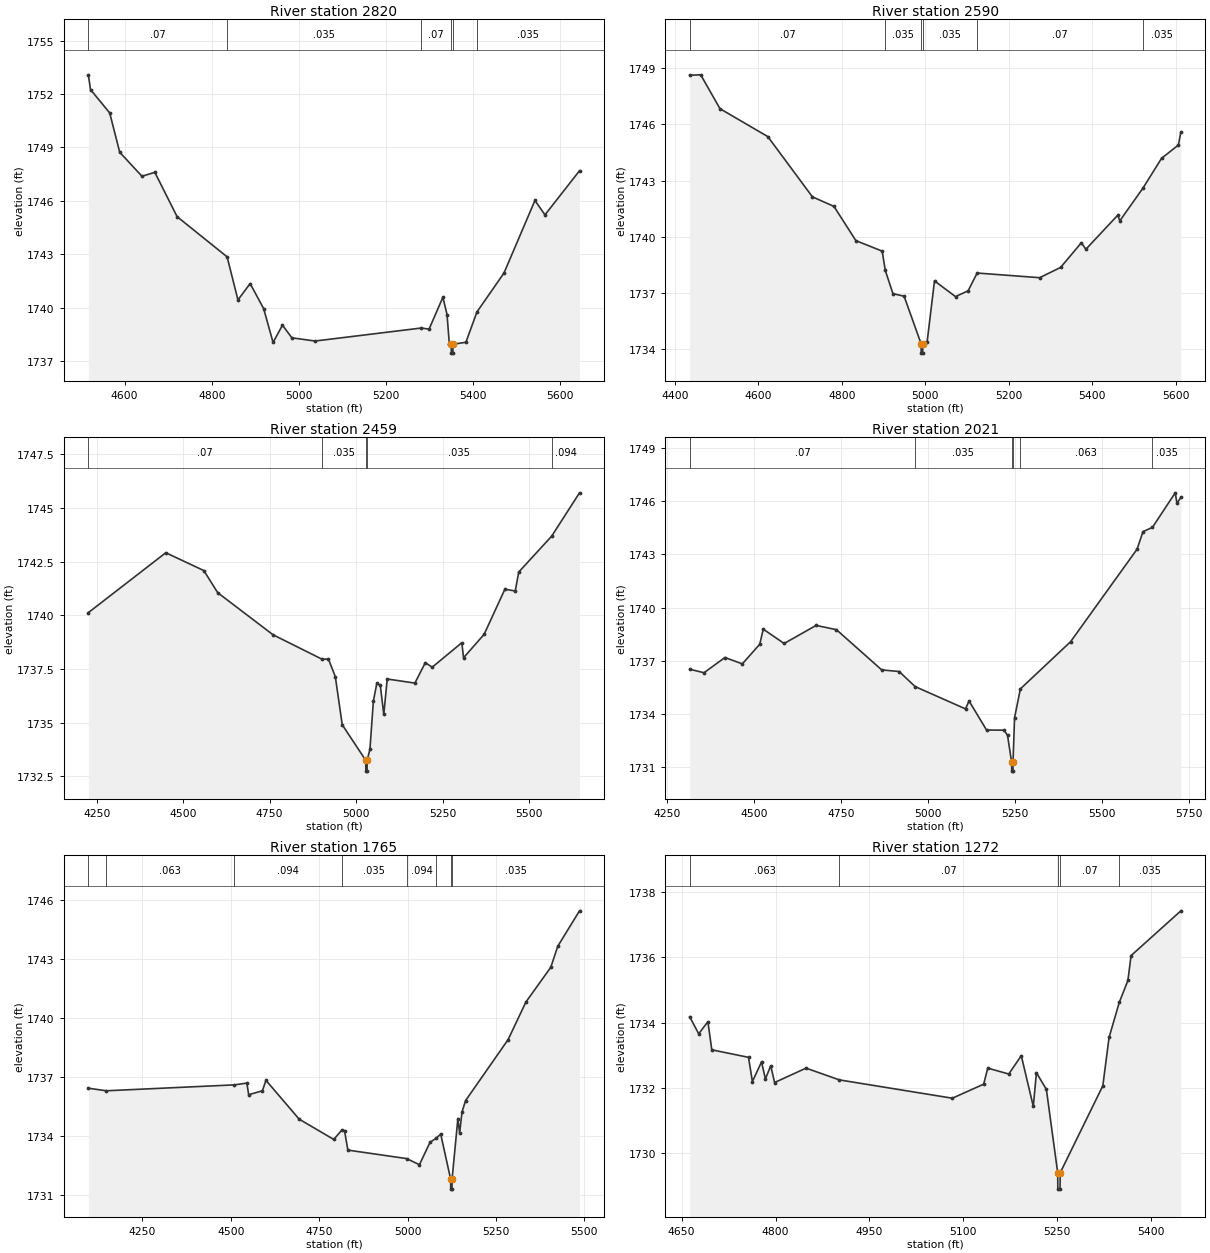
Type RM Length L Ch R = 1,2820,230,230,230
BEGIN DESCRIPTION:
Elm 01 44 2820.25
END DESCRIPTION:
XS GIS Cut Line= 3
      1557697.56      6852103.62      1557277.83      6851864.02
      1556668.13      6851656.32
#Sta/Elev= 30
  4516.7 1753.08  4521.7 1752.25  4565.7 1750.94  4588.7 1748.73  4639.8 1747.38
  4669.3 1747.60  4720.4 1745.11  4835.2 1742.85  4860.1 1740.43  4888.1 1741.35
  4919.1 1739.94  4940.7 1738.04  4962.3 1739.01  4983.9 1738.30  5037.1 1738.12
  5280.7 1738.85  5298.8 1738.79  5330.5 1740.58  5340.0 1739.61  5345.3 1737.95
  5349.6 1737.94  5349.9 1737.44  5353.4 1737.44  5353.6 1737.94  5383.3 1738.05
  5408.8 1739.76  5470.7 1741.94  5541.8 1746.02  5564.8 1745.21  5644.1 1747.69
#Mann=6,-1,0
  4516.7    0.07       0  4835.2   0.035       0  5280.7    0.07       0
  5349.6   0.035       0  5353.6    0.07       0  5408.8   0.035       0
Bank Sta=5349.6,5353.6
Exp/Cntr=0.3,0.1

Type RM Length L Ch R = 1,2590,131,131,131
BEGIN DESCRIPTION:
Elm 01 44 2590.25
END DESCRIPTION:
XS GIS Cut Line= 3
      1557944.09      6851881.40      1557402.41      6851707.78
      1556799.11      6851634.97
#Sta/Elev= 30
  4435.8 1748.63  4462.2 1748.65  4508.4 1746.84  4622.9 1745.35  4729.8 1742.13
  4781.4 1741.62  4833.9 1739.79  4896.9 1739.23  4904.3 1738.20  4922.6 1736.96
  4949.4 1736.82  4990.1 1734.28  4990.3 1733.78  4993.8 1733.78  4994.1 1734.28
  5004.6 1734.39  5022.2 1737.64  5072.5 1736.80  5102.7 1737.11  5124.4 1738.06
  5274.0 1737.81  5324.3 1738.36  5374.0 1739.68  5384.8 1739.33  5461.1 1741.15
  5466.1 1740.85  5521.9 1742.61  5566.1 1744.19  5606.4 1744.90  5612.3 1745.60
#Mann=6,-1,0
  4435.8    0.07       0  4904.3   0.035       0  4990.1   0.035       0
  4994.1   0.035       0  5124.4    0.07       0  5521.9   0.035       0
Bank Sta=4990.1,4994.1
Exp/Cntr=0.3,0.1

Type RM Length L Ch R = 1,2459,438,438,438
BEGIN DESCRIPTION:
Elm 01 44 2458.8
END DESCRIPTION:
XS GIS Cut Line= 3
      1558228.78      6851568.89      1557451.02      6851593.20
      1556809.30      6851614.01
#Sta/Elev= 30
  4225.7 1740.13  4449.6 1742.92  4559.6 1742.09  4599.7 1741.06  4759.7 1739.10
  4901.7 1737.96  4919.8 1737.97  4939.8 1737.15  4959.8 1734.91  5027.9 1733.25
  5028.1 1732.75  5031.6 1732.75  5031.9 1733.25  5039.9 1733.77  5049.9 1736.02
  5059.9 1736.84  5069.9 1736.74  5079.9 1735.39  5089.9 1737.04  5169.9 1736.85
  5200.0 1737.80  5220.0 1737.59  5305.6 1738.73  5310.6 1738.03  5370.1 1739.12
  5430.1 1741.22  5460.1 1741.14  5470.1 1742.02  5565.3 1743.69  5645.9 1745.71
#Mann=5,-1,0
  4225.7    0.07       0  4901.7   0.035       0  5027.9   0.035       0
  5031.9   0.035       0  5565.3   0.094       0
Bank Sta=5027.9,5031.9
Exp/Cntr=0.3,0.1

Type RM Length L Ch R = 1,2021,256,256,256
BEGIN DESCRIPTION:
Elm 01 44 2021.3
END DESCRIPTION:
XS GIS Cut Line= 3
      1558326.07      6851346.67      1557638.52      6851377.92
      1556919.93      6851454.29
#Sta/Elev= 30
  4315.7 1736.52  4356.8 1736.32  4416.9 1737.18  4466.9 1736.82  4517.0 1737.93
  4527.0 1738.78  4587.0 1737.97  4678.8 1738.99  4737.2 1738.75  4867.3 1736.48
  4917.4 1736.39  4963.3 1735.54  5108.1 1734.28  5118.1 1734.73  5168.4 1733.09
  5218.7 1733.08  5228.7 1732.79  5240.5 1731.27  5240.8 1730.77  5244.3 1730.77
  5244.5 1731.27  5248.9 1733.78  5265.6 1735.41  5409.8 1738.07  5600.8 1743.29
  5617.8 1744.28  5644.9 1744.52  5710.4 1746.47  5715.4 1745.88  5726.6 1746.21
#Mann=6,-1,0
  4315.7    0.07       0  4963.3   0.035       0  5240.5   0.035       0
  5244.5   0.035       0  5265.6   0.063       0  5644.9   0.035       0
Bank Sta=5240.5,5244.5
Exp/Cntr=0.3,0.1

Type RM Length L Ch R = 1,1765,493,493,493
BEGIN DESCRIPTION:
Elm 01 44 1764.76
END DESCRIPTION:
XS GIS Cut Line= 3
      1558402.41      6851315.42      1557510.05      6851190.42
      1557023.90      6851232.09
#Sta/Elev= 30
  4097.4 1736.43  4148.4 1736.30  4510.6 1736.60  4545.7 1736.69  4550.8 1736.10
  4589.6 1736.30  4599.7 1736.83  4693.6 1734.86  4791.5 1733.83  4813.8 1734.30
  4821.8 1734.28  4831.3 1733.29  4997.4 1732.86  5033.7 1732.55  5063.8 1733.69
  5081.7 1733.90  5093.9 1734.10  5122.0 1731.81  5122.2 1731.31  5125.7 1731.31
  5126.0 1731.81  5142.4 1734.89  5147.4 1734.16  5154.1 1735.22  5164.1 1735.80
  5284.6 1738.90  5334.7 1740.80  5405.0 1742.56  5425.1 1743.64  5486.4 1745.43
#Mann=8,-1,0
  4097.4    0.07       0  4148.4   0.063       0  4510.6   0.094       0
  4813.8   0.035       0  4997.4   0.094       0  5081.7   0.035       0
  5122.0    0.07       0  5126.0   0.035       0
Bank Sta=5122,5126
Exp/Cntr=0.3,0.1

Type RM Length L Ch R = 1,1272,114,114,114
BEGIN DESCRIPTION:
Elm 01 44 1251.63
END DESCRIPTION:
XS GIS Cut Line= 4
      1557942.31      6851040.99      1557722.57      6850880.94
      1557517.11      6850867.96      1557210.59      6850847.77
#Sta/Elev= 30
  4662.8 1734.18  4677.2 1733.66  4691.9 1734.03  4698.1 1733.17  4756.8 1732.94
  4763.0 1732.20  4777.6 1732.80  4783.8 1732.28  4792.3 1732.68  4798.5 1732.17
  4848.7 1732.61  4902.0 1732.25  5082.5 1731.69  5132.6 1732.12  5139.1 1732.61
  5172.7 1732.43  5192.7 1732.99  5211.9 1731.44  5216.9 1732.47  5232.8 1731.96
  5250.9 1729.41  5251.1 1728.91  5254.6 1728.91  5254.9 1729.41  5323.0 1732.07
  5333.0 1733.55  5349.3 1734.62  5363.1 1735.29  5368.1 1736.05  5447.7 1737.42
#Mann=5,-1,0
  4662.8   0.063       0  4902.0    0.07       0  5250.9    0.07       0
  5254.9    0.07       0  5349.3   0.035       0
Bank Sta=5250.9,5254.9
Exp/Cntr=0.3,0.1

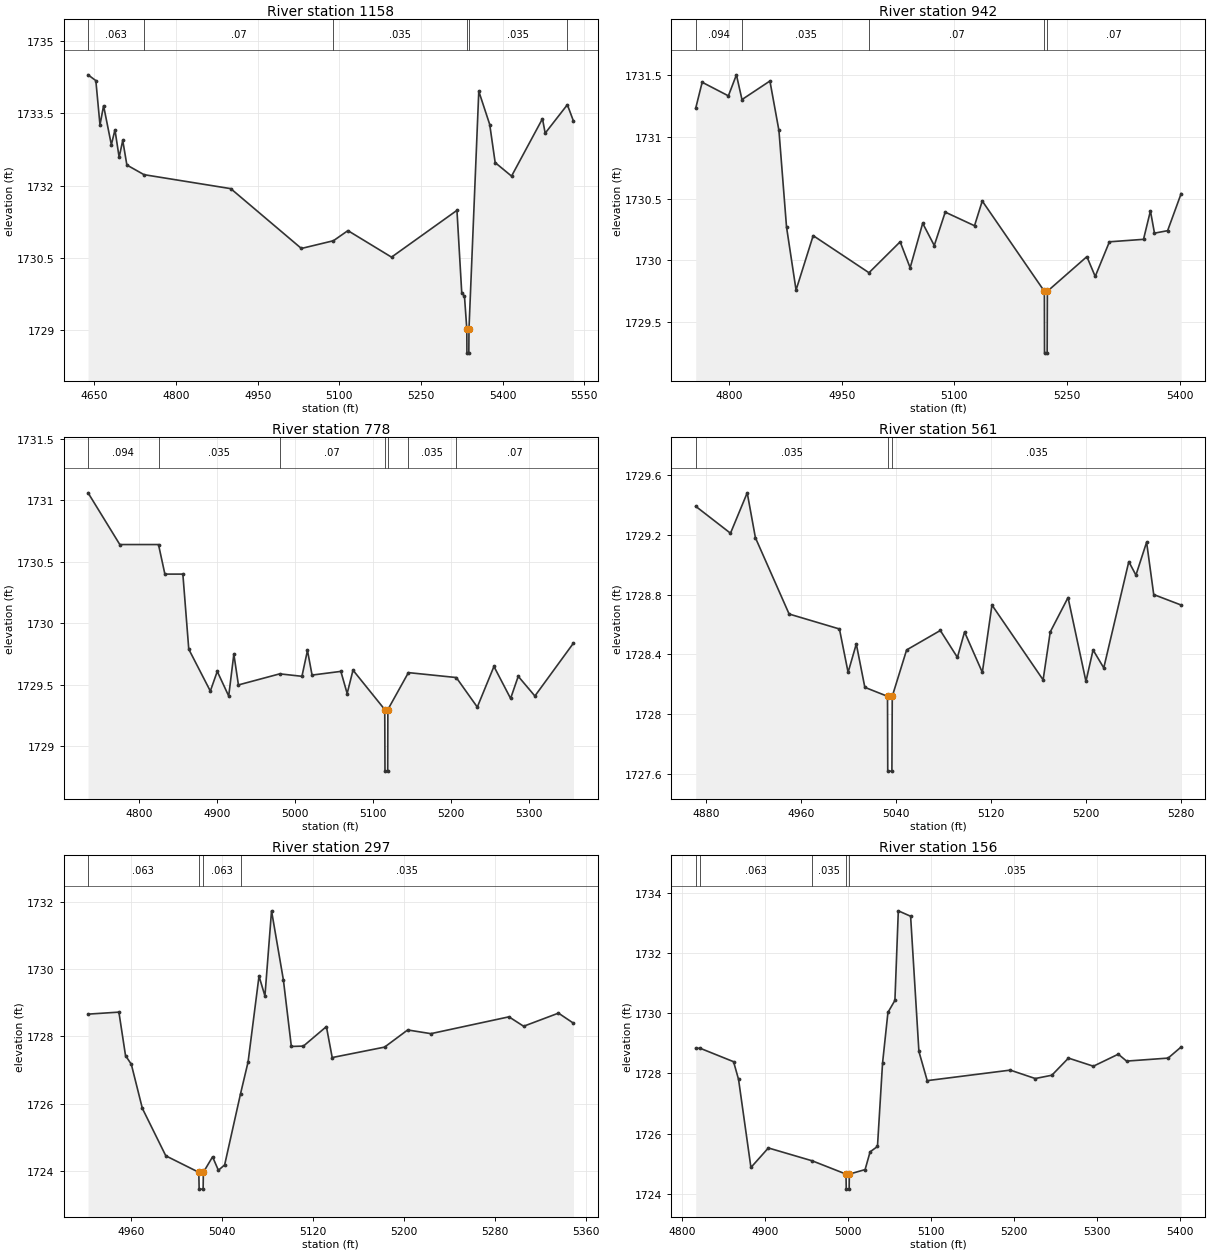
Type RM Length L Ch R = 1,1158,216,216,216
BEGIN DESCRIPTION:
Elm 01 44 1102.29
END DESCRIPTION:
XS GIS Cut Line= 4
      1557958.32      6851044.99      1557766.07      6850821.93
      1557609.10      6850717.17      1557201.45      6850689.21
#Sta/Elev= 30
  4638.3 1734.30  4652.6 1734.18  4660.2 1733.26  4666.8 1733.66  4681.1 1732.85
  4687.7 1733.16  4695.4 1732.59  4702.0 1732.94  4709.6 1732.43  4741.1 1732.23
  4900.5 1731.94  5030.2 1730.70  5089.0 1730.86  5115.7 1731.07  5195.8 1730.52
  5316.0 1731.49  5324.8 1729.78  5329.8 1729.71  5334.1 1729.03  5334.3 1728.53
  5337.8 1728.53  5338.1 1729.03  5356.1 1733.96  5376.2 1733.27  5386.2 1732.48
  5416.3 1732.20  5473.1 1733.39  5478.1 1733.09  5518.8 1733.68  5530.1 1733.34
#Mann=6,-1,0
  4638.3   0.063       0  4741.1    0.07       0  5089.0   0.035       0
  5334.1    0.07       0  5338.1   0.035       0  5518.8   0.063       0
Bank Sta=5334.1,5338.1
Exp/Cntr=0.3,0.1

Type RM Length L Ch R = 1,942,164,164,164
BEGIN DESCRIPTION:
Elm 01 44 941.96
END DESCRIPTION:
XS GIS Cut Line= 3
      1558114.36      6850788.28      1557891.99      6850683.48
      1557518.20      6850539.75
#Sta/Elev= 30
  4755.7 1731.23  4764.3 1731.44  4799.2 1731.33  4809.9 1731.50  4817.3 1731.30
  4854.5 1731.45  4866.5 1731.05  4876.6 1730.27  4889.3 1729.76  4912.1 1730.20
  4986.4 1729.90  5027.9 1730.15  5041.2 1729.94  5057.9 1730.30  5073.3 1730.12
  5087.9 1730.39  5126.9 1730.28  5137.2 1730.48  5219.9 1729.75  5220.1 1729.25
  5223.6 1729.25  5223.9 1729.75  5276.5 1730.03  5287.6 1729.87  5306.5 1730.15
  5351.9 1730.17  5361.1 1730.40  5366.5 1730.22  5384.0 1730.24  5402.0 1730.54
#Mann=5,-1,0
  4755.7   0.094       0  4817.3   0.035       0  4986.4    0.07       0
  5219.9    0.07       0  5223.9    0.07       0
Bank Sta=5219.9,5223.9
Exp/Cntr=0.3,0.1

Type RM Length L Ch R = 1,778,217,217,217
BEGIN DESCRIPTION:
Elm 01 44 777.94
END DESCRIPTION:
XS GIS Cut Line= 3
      1558118.48      6850692.21      1557891.99      6850551.53
      1557585.05      6850369.07
#Sta/Elev= 30
  4734.0 1731.06  4774.8 1730.64  4824.5 1730.64  4832.7 1730.40  4855.8 1730.40
  4863.4 1729.79  4891.1 1729.45  4900.0 1729.61  4914.7 1729.41  4921.3 1729.75
  4927.2 1729.50  4980.3 1729.59  5008.8 1729.57  5015.9 1729.78  5021.8 1729.58
  5058.8 1729.61  5066.9 1729.43  5074.4 1729.62  5115.2 1729.30  5115.5 1728.80
  5119.0 1728.80  5119.2 1729.30  5145.6 1729.60  5207.1 1729.56  5234.1 1729.32
  5255.5 1729.65  5276.9 1729.39  5286.7 1729.57  5308.1 1729.41  5357.7 1729.84
#Mann=7,-1,0
  4734.0   0.094       0  4824.5   0.035       0  4980.3    0.07       0
  5115.2    0.07       0  5119.2    0.07       0  5145.6   0.035       0
  5207.1    0.07       0
Bank Sta=5115.2,5119.2
Exp/Cntr=0.3,0.1

Type RM Length L Ch R = 1,561,264,264,264
BEGIN DESCRIPTION:
Elm 01 44 559.76
END DESCRIPTION:
XS GIS Cut Line= 3
      1558151.70      6850522.63      1558002.81      6850365.88
      1557842.12      6850259.33
#Sta/Elev= 30
  4871.0 1729.39  4900.3 1729.21  4914.4 1729.48  4921.3 1729.18  4949.7 1728.67
  4992.1 1728.57  4999.4 1728.28  5006.3 1728.47  5013.5 1728.18  5032.6 1728.12
  5032.8 1727.62  5036.3 1727.62  5036.6 1728.12  5048.7 1728.43  5077.1 1728.56
  5091.5 1728.38  5097.5 1728.55  5112.5 1728.28  5120.6 1728.73  5163.7 1728.23
  5169.7 1728.55  5184.7 1728.78  5199.8 1728.22  5205.8 1728.43  5214.8 1728.31
  5235.9 1729.02  5241.9 1728.93  5250.9 1729.15  5256.9 1728.80  5280.0 1728.73
#Mann=3,-1,0
  4871.0   0.035       0  5032.6   0.035       0  5036.6   0.035       0
Bank Sta=5032.6,5036.6
Exp/Cntr=0.3,0.1

Type RM Length L Ch R = 1,297,141,141,141
BEGIN DESCRIPTION:
Elm 01 44 1.0
END DESCRIPTION:
XS GIS Cut Line= 3
      1558278.31      6850454.22      1558233.62      6850279.44
      1557992.00      6850232.70
#Sta/Elev= 30
  4922.2 1728.66  4949.3 1728.72  4955.1 1727.43  4960.2 1727.17  4969.9 1725.86
  4990.5 1724.45  5019.5 1723.96  5019.8 1723.46  5023.3 1723.46  5023.5 1723.96
  5031.6 1724.42  5036.7 1724.02  5042.2 1724.18  5056.2 1726.30  5062.8 1727.24
  5072.4 1729.79  5077.6 1729.20  5083.4 1731.73  5093.8 1729.68  5100.8 1727.70
  5111.4 1727.71  5131.6 1728.29  5136.7 1727.37  5182.7 1727.68  5203.0 1728.19
  5223.4 1728.08  5292.0 1728.58  5304.9 1728.30  5335.5 1728.69  5348.7 1728.39
#Mann=4,-1,0
  4922.2   0.063       0  5019.5   0.063       0  5023.5   0.063       0
  5056.2   0.035       0
Bank Sta=5019.5,5023.5
Exp/Cntr=0.3,0.1

Type RM Length L Ch R = 1,156,0,0,0
BEGIN DESCRIPTION:
Elm 01 44 160.303
END DESCRIPTION:
XS GIS Cut Line= 3
      1558456.80      6850429.04      1558317.92      6850226.18
      1557979.36      6850214.74
#Sta/Elev= 30
  4816.5 1728.83  4821.6 1728.84  4862.1 1728.39  4868.1 1727.80  4883.0 1724.87
  4904.0 1725.52  4957.0 1725.09  4997.5 1724.65  4997.8 1724.15  5001.3 1724.15
  5001.5 1724.65  5020.5 1724.80  5026.5 1725.39  5035.4 1725.57  5041.5 1728.34
  5048.0 1730.03  5056.4 1730.43  5060.5 1733.41  5075.3 1733.23  5085.3 1728.73
  5095.3 1727.76  5195.3 1728.11  5225.4 1727.83  5245.4 1727.94  5265.4 1728.51
  5295.4 1728.24  5325.4 1728.64  5335.4 1728.41  5385.4 1728.51  5401.1 1728.88
#Mann=5,-1,0
  4816.5   0.035       0  4821.6   0.063       0  4957.0   0.035       0
  4997.5   0.035       0  5001.5   0.035       0
Bank Sta=4997.5,5001.5
Exp/Cntr=0.3,0.1

Chan Stop Cuts=-1