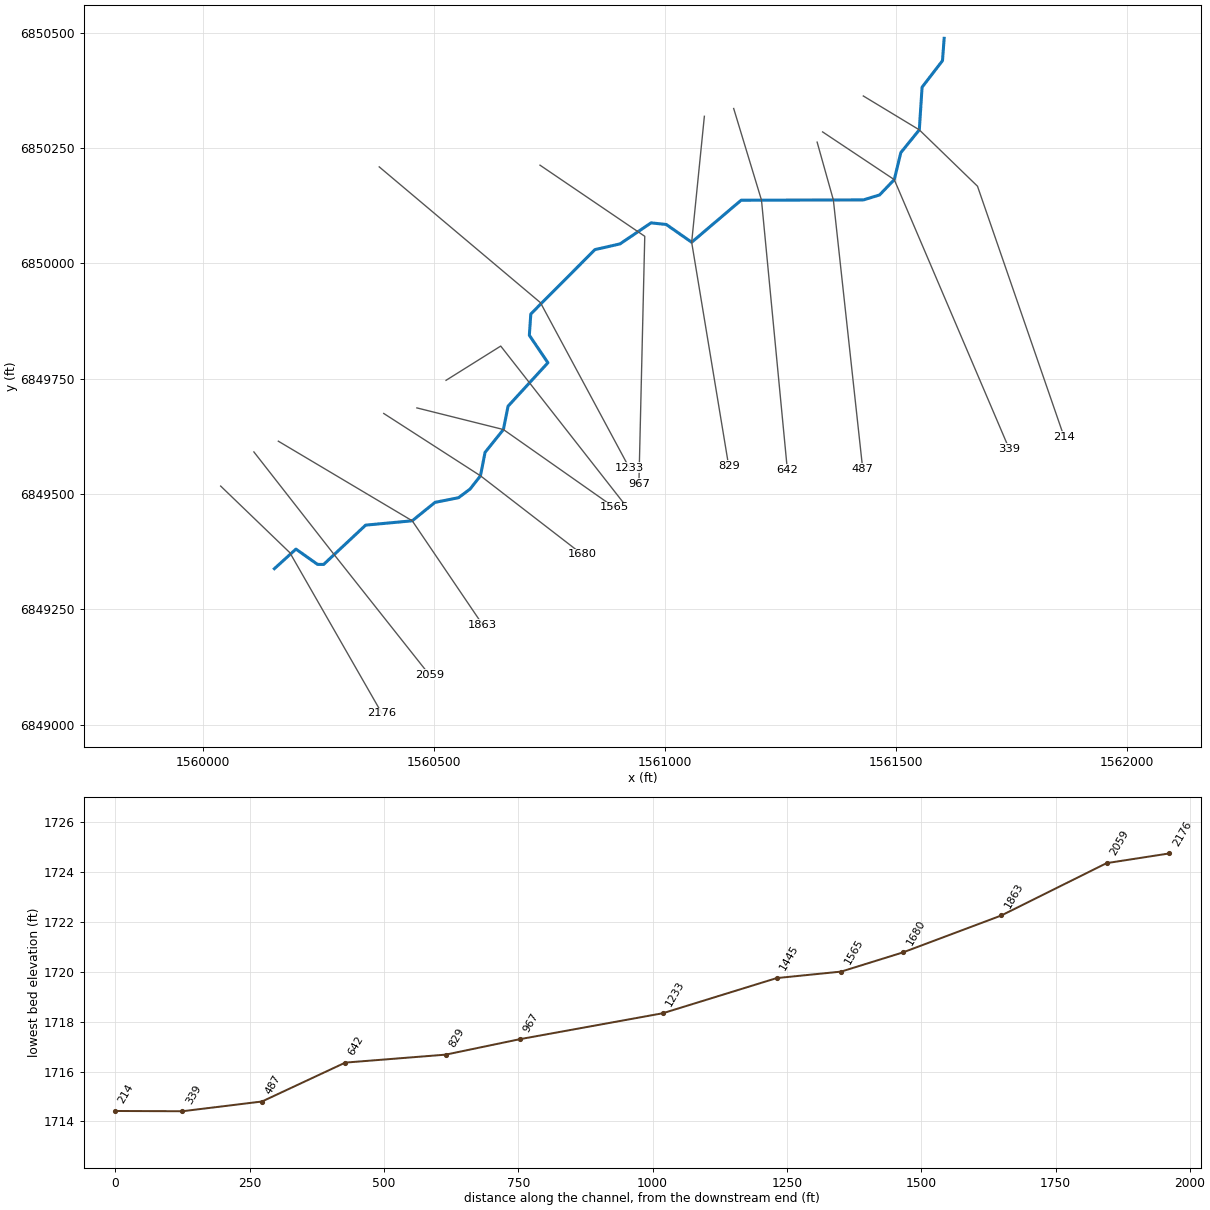
--- Elm 01 45.prj (project) ---

Proj Title=Elm 01 45 Base Level Engineering
Current Plan=p01
Default Exp/Contr=0.3,0.1
English Units
Geom File=g01
Flow File=f01
Plan File=p01
BEGIN DESCRIPTION:
Elm 01 45
END DESCRIPTION:

--- Elm 01 45.p01 (plan) ---

Plan Title=Multiple Run
Short Identifier=Multiple
Geom File=g01
Flow File=f01
Subcritical Flow
K Sum by GR= 0
Std Step Tol= 0.01
Critical Tol= 0.01
Num of Std Step Trials= 20
Max Error Tol= 0.3
Flow Tol Ratio= 0.001
Split Flow NTrial= 30
Split Flow Tol= 0.02
Split Flow Ratio= 0.02
Log Output Level= 0
Friction Slope Method= 1
Unsteady Friction Slope Method= 2
Unsteady Bridges Friction Slope Method= 1
Parabolic Critical Depth
Global Vel Dist=  1 , 1 , 1
Global Log Level= 0
CheckData=True
Encroach Param= -1, 0, 0, 0
BEGIN DESCRIPTION:
Multiple Run
END DESCRIPTION:

--- Elm 01 45.f01 (steady flow) ---

Flow Title=Multiple
Number of Profiles=7
Profile Names=10-year,25-year,50-year,1pct_min,100-year,1pct_plu,500-year
River Rch & RM= Elm 01 45,Reach-1,2176
      93     120     142     104     167     230     233
Boundary for River Rch & Prof#=Elm 01 45,Reach-1,1
Up Type=0
Dn Type=3
Dn Slope=0.005
Boundary for River Rch & Prof#=Elm 01 45,Reach-1,2
Up Type=0
Dn Type=3
Dn Slope=0.005
Boundary for River Rch & Prof#=Elm 01 45,Reach-1,3
Up Type=0
Dn Type=3
Dn Slope=0.005
Boundary for River Rch & Prof#=Elm 01 45,Reach-1,4
Up Type=0
Dn Type=3
Dn Slope=0.005
Boundary for River Rch & Prof#=Elm 01 45,Reach-1,5
Up Type=0
Dn Type=3
Dn Slope=0.005
Boundary for River Rch & Prof#=Elm 01 45,Reach-1,6
Up Type=0
Dn Type=3
Dn Slope=0.005
Boundary for River Rch & Prof#=Elm 01 45,Reach-1,7
Up Type=0
Dn Type=3
Dn Slope=0.005

--- Elm 01 45.g01 (geometry) ---

Geom Title=Existing Conditions

River Reach=Elm 01 45,Reach-1
Reach XY= 30
      1560155.00      6849338.00      1560201.67      6849380.48
      1560248.33      6849347.36      1560261.66      6849347.21
      1560352.57      6849432.45      1560453.42      6849441.83
      1560502.85      6849481.85      1560553.58      6849491.86
      1560578.84      6849510.85      1560601.14      6849539.42
      1560611.11      6849590.16      1560650.81      6849639.73
      1560660.86      6849690.30      1560747.17      6849784.60
      1560706.99      6849844.05      1560710.12      6849890.29
      1560848.94      6850029.86      1560903.26      6850042.25
      1560970.41      6850087.86      1561003.37      6850084.39
      1561058.40      6850045.83      1561165.43      6850136.94
      1561430.21      6850137.67      1561465.12      6850148.34
      1561497.00      6850181.61      1561511.15      6850240.15
      1561551.18      6850289.58      1561557.23      6850382.08
      1561601.36      6850439.51      1561605.00      6850488.00

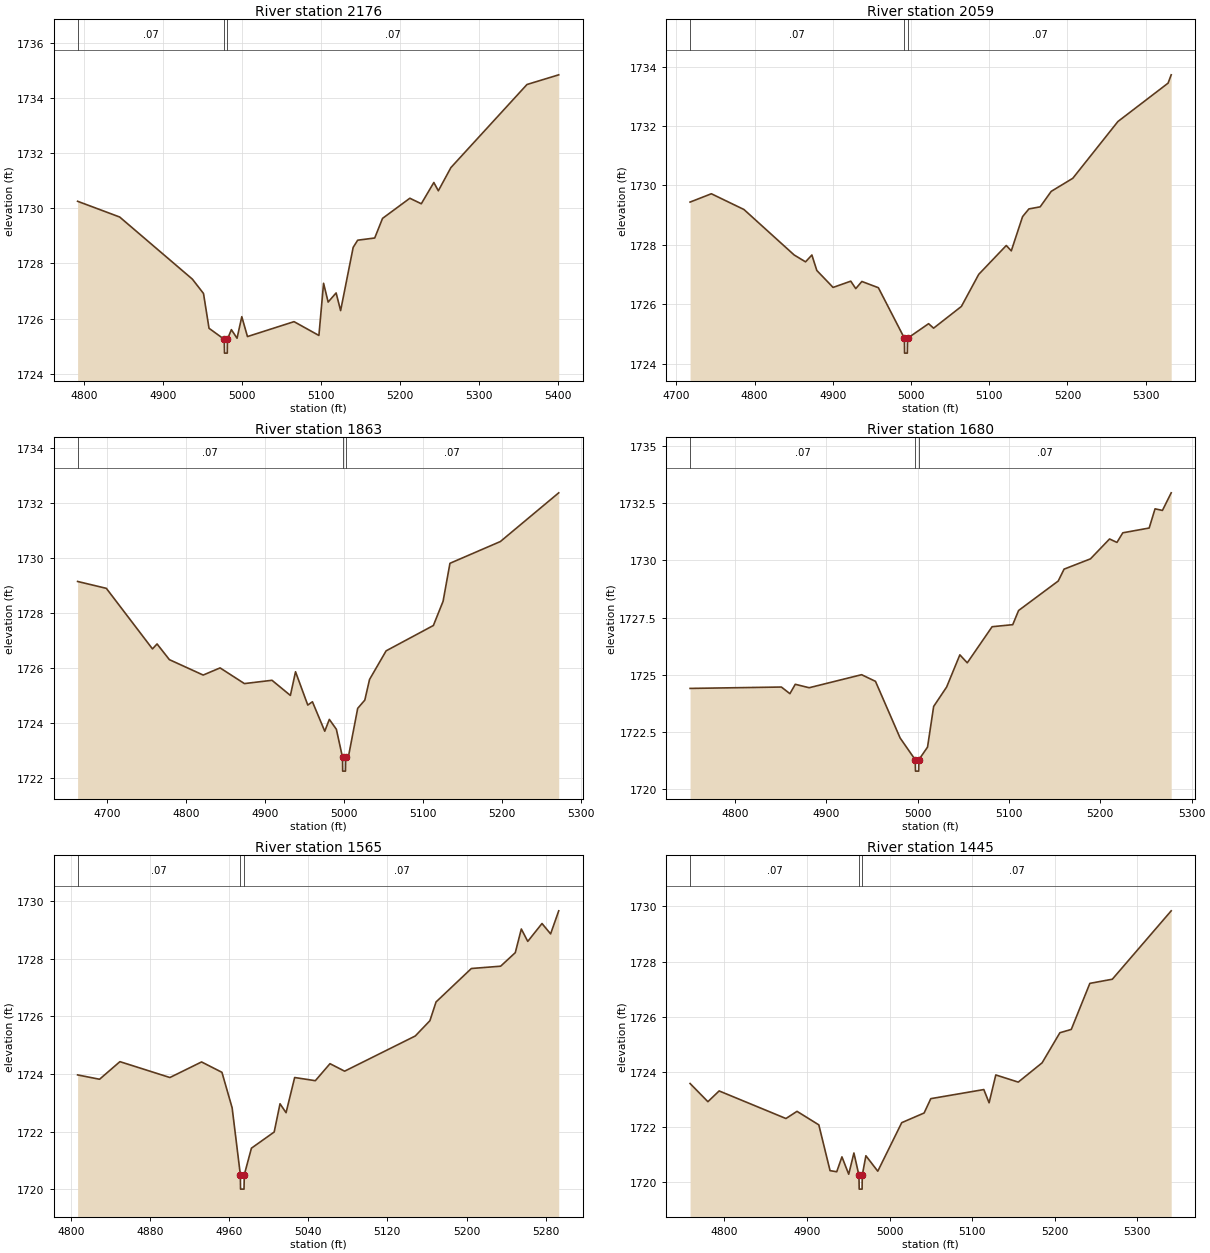
Type RM Length L Ch R = 1,2176,117,117,117
BEGIN DESCRIPTION:
Elm 01 45 2176.462
END DESCRIPTION:
XS GIS Cut Line= 3
      1560038.70      6849517.16      1560188.62      6849372.55
      1560387.76      6849024.26
#Sta/Elev= 30
  4791.7 1730.25  4845.0 1729.68  4937.1 1727.43  4951.2 1726.91  4958.2 1725.65
  4977.5 1725.25  4977.8 1724.75  4981.3 1724.75  4981.5 1725.25  4986.5 1725.60
  4993.7 1725.29  4999.7 1726.07  5006.9 1725.35  5065.9 1725.89  5097.4 1725.39
  5103.3 1727.28  5109.1 1726.60  5119.2 1726.93  5124.9 1726.29  5140.8 1728.58
  5146.5 1728.84  5168.1 1728.92  5178.0 1729.63  5212.6 1730.36  5227.1 1730.16
  5243.0 1730.93  5248.7 1730.63  5264.6 1731.47  5361.0 1734.48  5401.2 1734.83
#Mann=3,-1,0
  4791.7    0.07       0  4977.5    0.07       0  4981.5    0.07       0
Bank Sta=4977.5,4981.5
Exp/Cntr=0.3,0.1

Type RM Length L Ch R = 1,2059,196,196,196
BEGIN DESCRIPTION:
Elm 01 45 2058.647
END DESCRIPTION:
XS GIS Cut Line= 3
      1560110.66      6849591.16      1560284.39      6849368.52
      1560490.71      6849107.65
#Sta/Elev= 30
  4717.6 1729.44  4744.8 1729.72  4786.5 1729.19  4850.7 1727.66  4865.2 1727.43
  4873.3 1727.66  4879.6 1727.14  4900.4 1726.57  4923.0 1726.78  4929.4 1726.53
  4937.2 1726.77  4958.3 1726.56  4991.6 1724.86  4991.8 1724.36  4995.3 1724.36
  4995.6 1724.86  5022.5 1725.35  5028.9 1725.20  5064.4 1725.93  5086.6 1727.01
  5121.8 1727.98  5128.2 1727.80  5142.6 1728.95  5150.7 1729.21  5165.1 1729.28
  5179.2 1729.80  5206.8 1730.24  5264.5 1732.15  5328.6 1733.44  5332.6 1733.72
#Mann=3,-1,0
  4717.6    0.07       0  4991.6    0.07       0  4995.6    0.07       0
Bank Sta=4991.6,4995.6
Exp/Cntr=0.3,0.1

Type RM Length L Ch R = 1,1863,183,183,183
BEGIN DESCRIPTION:
Elm 01 45 1863.289
END DESCRIPTION:
XS GIS Cut Line= 3
      1560163.53      6849614.46      1560453.42      6849441.83
      1560605.64      6849216.78
#Sta/Elev= 30
  4662.6 1729.15  4699.0 1728.90  4757.4 1726.70  4763.2 1726.88  4778.8 1726.31
  4821.6 1725.75  4843.0 1726.01  4873.8 1725.44  4908.7 1725.56  4932.0 1725.01
  4938.5 1725.87  4954.0 1724.66  4959.9 1724.78  4975.5 1723.71  4981.3 1724.14
  4990.2 1723.78  4998.0 1722.76  4998.2 1722.26  5001.7 1722.26  5002.0 1722.76
  5005.3 1722.76  5017.2 1724.54  5026.2 1724.84  5032.2 1725.59  5053.2 1726.63
  5113.0 1727.55  5125.3 1728.43  5134.0 1729.81  5197.8 1730.60  5271.7 1732.37
#Mann=3,-1,0
  4662.6    0.07       0  4998.0    0.07       0  5002.0    0.07       0
Bank Sta=4998,5002
Exp/Cntr=0.3,0.1

Type RM Length L Ch R = 1,1680,115,115,115
BEGIN DESCRIPTION:
Elm 01 45 1680.127
END DESCRIPTION:
XS GIS Cut Line= 3
      1560391.77      6849674.57      1560601.14      6849539.42
      1560820.75      6849369.61
#Sta/Elev= 30
  4750.8 1724.40  4850.8 1724.46  4860.1 1724.17  4866.0 1724.58  4881.2 1724.43
  4938.6 1725.00  4953.8 1724.71  4980.8 1722.23  4997.3 1721.28  4997.6 1720.78
  5001.1 1720.78  5001.3 1721.28  5010.8 1721.83  5017.5 1723.61  5031.7 1724.46
  5046.2 1725.87  5054.3 1725.52  5081.5 1727.10  5104.1 1727.19  5110.5 1727.81
  5153.9 1729.10  5160.3 1729.62  5189.2 1730.07  5210.1 1730.94  5218.2 1730.79
  5224.6 1731.21  5253.5 1731.42  5259.9 1732.26  5268.0 1732.19  5277.6 1732.96
#Mann=3,-1,0
  4750.8    0.07       0  4997.3    0.07       0  5001.3    0.07       0
Bank Sta=4997.3,5001.3
Exp/Cntr=0.3,0.1

Type RM Length L Ch R = 1,1565,120,120,120
BEGIN DESCRIPTION:
Elm 01 45 1564.905
END DESCRIPTION:
XS GIS Cut Line= 3
      1560463.50      6849686.65      1560650.81      6849639.73
      1560890.63      6849471.05
#Sta/Elev= 30
  4806.9 1723.97  4829.1 1723.82  4849.7 1724.43  4900.2 1723.88  4932.2 1724.42
  4952.8 1724.06  4963.1 1722.83  4971.4 1720.51  4971.6 1720.01  4975.1 1720.01
  4975.4 1720.51  4982.6 1721.43  5005.6 1721.99  5011.5 1722.97  5017.6 1722.66
  5026.3 1723.88  5047.2 1723.77  5062.0 1724.36  5076.8 1724.10  5148.2 1725.32
  5163.0 1725.85  5169.2 1726.50  5204.9 1727.66  5234.5 1727.74  5249.3 1728.21
  5255.4 1729.03  5261.9 1728.60  5276.3 1729.22  5285.0 1728.86  5293.2 1729.66
#Mann=3,-1,0
  4806.9    0.07       0  4971.4    0.07       0  4975.4    0.07       0
Bank Sta=4971.4,4975.4
Exp/Cntr=0.3,0.1

Type RM Length L Ch R = 1,1445,212,212,212
BEGIN DESCRIPTION:
Elm 01 45 1405.384
END DESCRIPTION:
XS GIS Cut Line= 3
      1560526.66      6849746.48      1560645.02      6849820.72
      1560917.81      6849471.82
#Sta/Elev= 30
  4758.5 1723.58  4780.1 1722.92  4793.7 1723.31  4874.6 1722.31  4888.0 1722.57
  4914.4 1722.08  4928.0 1720.42  4936.1 1720.38  4942.4 1720.92  4950.6 1720.29
  4956.9 1721.06  4963.0 1720.25  4963.3 1719.75  4966.8 1719.75  4967.0 1720.25
  4971.4 1720.96  4985.8 1720.40  5014.8 1722.16  5041.9 1722.51  5050.0 1723.03
  5114.2 1723.36  5120.6 1722.88  5128.7 1723.89  5155.9 1723.63  5184.8 1724.33
  5206.3 1725.42  5220.1 1725.54  5242.6 1727.21  5269.8 1727.36  5341.1 1729.84
#Mann=3,-1,0
  4758.5    0.07       0  4963.0    0.07       0  4967.0    0.07       0
Bank Sta=4963,4967
Exp/Cntr=0.3,0.1

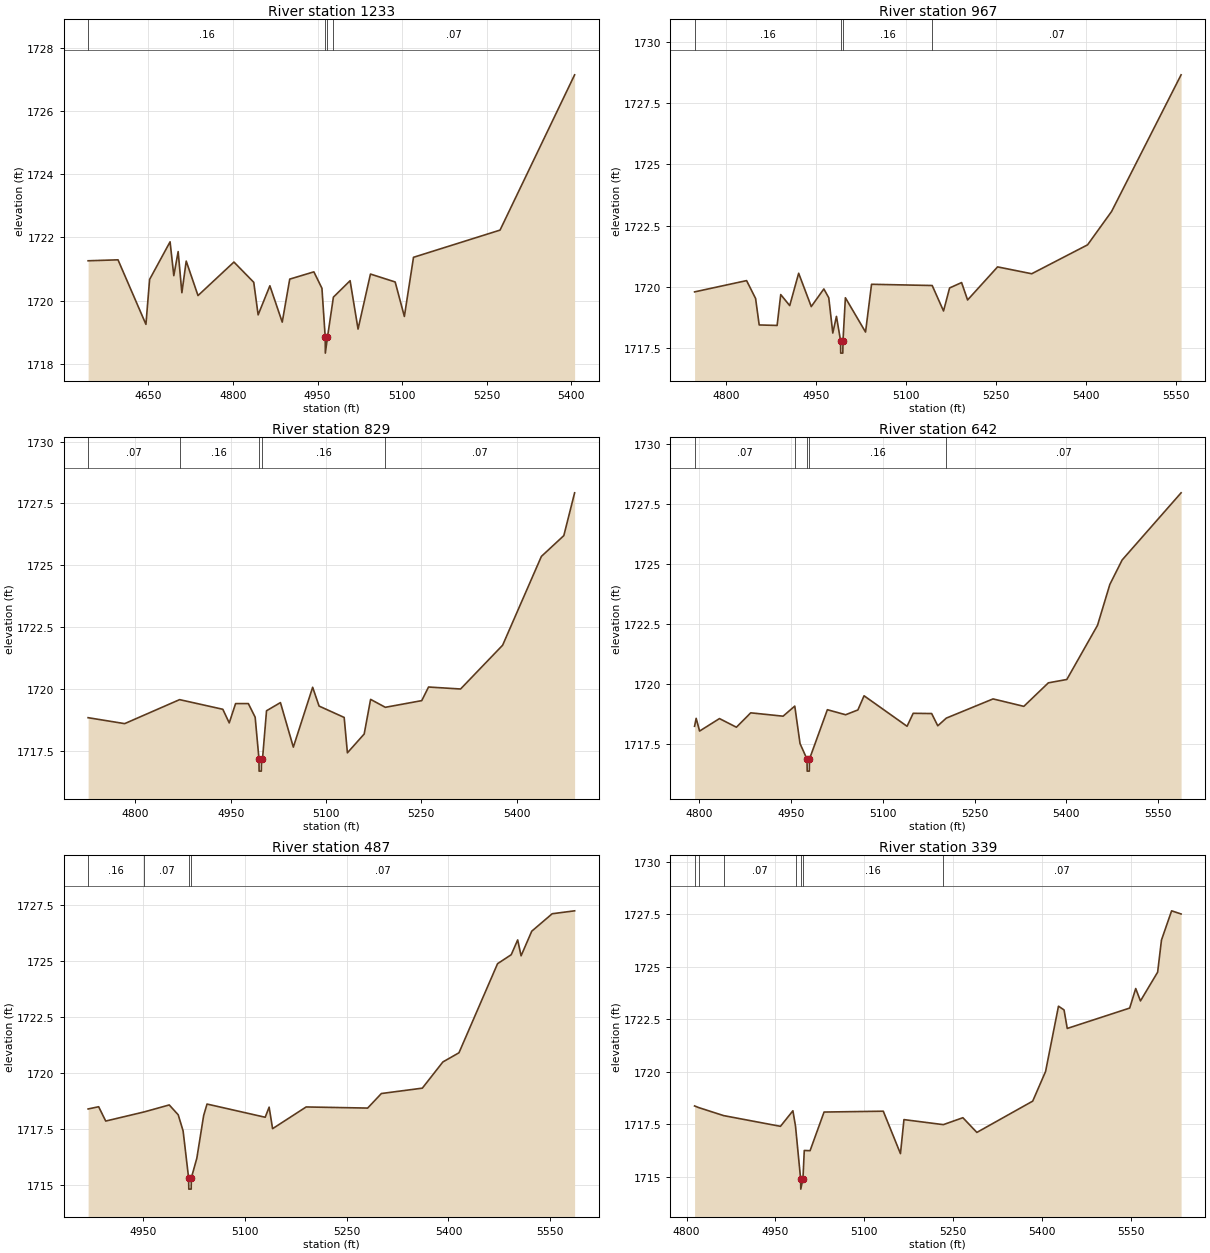
Type RM Length L Ch R = 1,1233,266,266,266
BEGIN DESCRIPTION:
Elm 01 45 1232.946
END DESCRIPTION:
XS GIS Cut Line= 3
      1560381.96      6850209.30      1560731.04      6849914.82
      1560922.97      6849557.39
#Sta/Elev= 30
  4543.3 1721.26  4596.3 1721.29  4645.8 1719.25  4652.3 1720.67  4688.6 1721.86
  4695.2 1720.79  4702.9 1721.55  4709.5 1720.25  4717.2 1721.25  4738.1 1720.16
  4801.8 1721.22  4836.9 1720.58  4844.7 1719.55  4865.5 1720.47  4887.4 1719.32
  4900.7 1720.68  4943.5 1720.91  4957.8 1720.39  4963.6 1718.84  4963.8 1718.34
  4967.6 1718.84  4978.1 1720.11  5007.7 1720.63  5021.8 1719.10  5043.8 1720.84
  5087.6 1720.59  5103.9 1719.50  5120.1 1721.37  5273.5 1722.23  5405.7 1727.14
#Mann=4,-1,0
  4543.3    0.16       0  4963.6    0.07       0  4967.6    0.16       0
  4978.1    0.07       0
Bank Sta=4963.6,4967.6
Exp/Cntr=0.3,0.1

Type RM Length L Ch R = 1,967,138,138,138
BEGIN DESCRIPTION:
Elm 01 45 966.568
END DESCRIPTION:
XS GIS Cut Line= 3
      1560730.04      6850212.97      1560956.84      6850058.73
      1560944.16      6849522.16
#Sta/Elev= 30
  4748.1 1719.80  4834.8 1720.26  4849.8 1719.53  4855.8 1718.45  4885.7 1718.43
  4891.7 1719.69  4906.7 1719.24  4921.6 1720.56  4942.6 1719.20  4963.6 1719.92
  4971.8 1719.56  4978.5 1718.12  4984.6 1718.80  4991.5 1717.80  4991.7 1717.30
  4995.2 1717.30  4995.5 1717.80  4999.5 1719.56  5033.1 1718.16  5043.1 1720.11
  5144.2 1720.06  5163.1 1719.02  5173.2 1719.96  5193.2 1720.18  5203.2 1719.47
  5253.2 1720.82  5310.1 1720.54  5403.2 1721.72  5443.2 1723.08  5559.1 1728.66
#Mann=4,-1,0
  4748.1    0.16       0  4991.5    0.07       0  4995.5    0.16       0
  5144.2    0.07       0
Bank Sta=4991.5,4995.5
Exp/Cntr=0.3,0.1

Type RM Length L Ch R = 1,829,187,187,187
BEGIN DESCRIPTION:
Elm 01 45 828.584
END DESCRIPTION:
XS GIS Cut Line= 3
      1561085.89      6850318.96      1561058.40      6850045.83
      1561138.48      6849561.21
#Sta/Elev= 30
  4725.5 1718.84  4783.0 1718.60  4869.5 1719.57  4937.5 1719.18  4947.6 1718.63
  4957.6 1719.41  4977.7 1719.41  4988.4 1718.86  4994.4 1717.18  4994.6 1716.68
  4998.1 1716.68  4998.4 1717.18  5000.0 1717.18  5006.3 1719.12  5028.2 1719.45
  5048.5 1717.65  5078.9 1720.07  5089.0 1719.31  5128.5 1718.85  5133.6 1717.42
  5160.0 1718.18  5170.1 1719.58  5193.3 1719.26  5250.6 1719.53  5261.3 1720.08
  5311.7 1720.00  5377.9 1721.77  5438.9 1725.36  5474.2 1726.20  5491.2 1727.93
#Mann=5,-1,0
  4725.5    0.07       0  4869.5    0.16       0  4994.4    0.07       0
  4998.4    0.16       0  5193.3    0.07       0
Bank Sta=4994.4,4998.4
Exp/Cntr=0.3,0.1

Type RM Length L Ch R = 1,642,155,155,155
BEGIN DESCRIPTION:
Elm 01 45 642.484
END DESCRIPTION:
XS GIS Cut Line= 3
      1561149.36      6850335.84      1561209.56      6850137.06
      1561265.60      6849552.04
#Sta/Elev= 30
  4792.3 1718.23  4794.9 1718.56  4800.5 1718.03  4833.0 1718.55  4860.7 1718.19
  4884.1 1718.79  4937.0 1718.65  4956.1 1719.07  4964.7 1717.51  4976.1 1716.86
  4976.4 1716.36  4979.9 1716.36  4980.1 1716.86  5009.4 1718.92  5039.2 1718.71
  5059.3 1718.91  5069.4 1719.50  5139.7 1718.23  5149.7 1718.77  5179.9 1718.76
  5189.9 1718.25  5203.9 1718.57  5280.3 1719.37  5330.6 1719.06  5370.7 1720.04
  5400.9 1720.18  5451.1 1722.44  5471.2 1724.14  5491.3 1725.16  5587.7 1727.96
#Mann=5,-1,0
  4792.3    0.07       0  4956.1    0.16       0  4976.1    0.07       0
  4980.1    0.16       0  5203.9    0.07       0
Bank Sta=4976.1,4980.1
Exp/Cntr=0.3,0.1

Type RM Length L Ch R = 1,487,148,148,148
BEGIN DESCRIPTION:
Elm 01 45 486.886
END DESCRIPTION:
XS GIS Cut Line= 3
      1561330.01      6850262.96      1561365.16      6850137.49
      1561428.60      6849555.23
#Sta/Elev= 30
  4869.7 1718.38  4885.2 1718.48  4895.6 1717.84  4952.4 1718.25  4989.1 1718.56
  5002.3 1718.12  5009.5 1717.40  5017.6 1715.30  5017.9 1714.80  5021.4 1714.80
  5021.6 1715.30  5029.7 1716.18  5039.7 1718.08  5044.7 1718.60  5130.3 1718.01
  5136.1 1718.46  5141.2 1717.50  5190.6 1718.47  5281.1 1718.42  5301.3 1719.07
  5361.6 1719.31  5391.8 1720.48  5415.5 1720.89  5472.3 1724.87  5492.4 1725.27
  5501.9 1725.93  5506.9 1725.22  5522.6 1726.32  5552.7 1727.10  5585.7 1727.23
#Mann=4,-1,0
  4869.7    0.16       0  4952.4    0.07       0  5017.6    0.07       0
  5021.6    0.07       0
Bank Sta=5017.6,5021.6
Exp/Cntr=0.3,0.1

Type RM Length L Ch R = 1,339,125,125,125
BEGIN DESCRIPTION:
Elm 01 45 338.633
END DESCRIPTION:
XS GIS Cut Line= 3
      1561341.84      6850285.10      1561497.00      6850181.61
      1561745.92      6849597.55
#Sta/Elev= 30
  4813.5 1718.37  4820.7 1718.29  4862.6 1717.91  4958.5 1717.40  4979.5 1718.14
  4983.9 1717.41  4992.5 1714.91  4992.8 1714.41  4996.5 1714.91  4998.7 1716.25
  5008.5 1716.24  5032.1 1718.08  5132.1 1718.12  5161.1 1716.10  5167.0 1717.72
  5233.5 1717.48  5266.5 1717.81  5290.1 1717.11  5384.4 1718.60  5406.1 1720.01
  5427.9 1723.12  5437.3 1722.94  5442.7 1722.06  5548.1 1723.03  5558.3 1723.96
  5566.3 1723.37  5595.3 1724.74  5601.8 1726.27  5618.9 1727.66  5634.9 1727.51
#Mann=7,-1,0
  4813.5    0.07       0  4820.7    0.16       0  4862.6    0.07       0
  4983.9    0.16       0  4992.5    0.07       0  4996.5    0.16       0
  5233.5    0.07       0
Bank Sta=4992.5,4996.5
Exp/Cntr=0.3,0.1

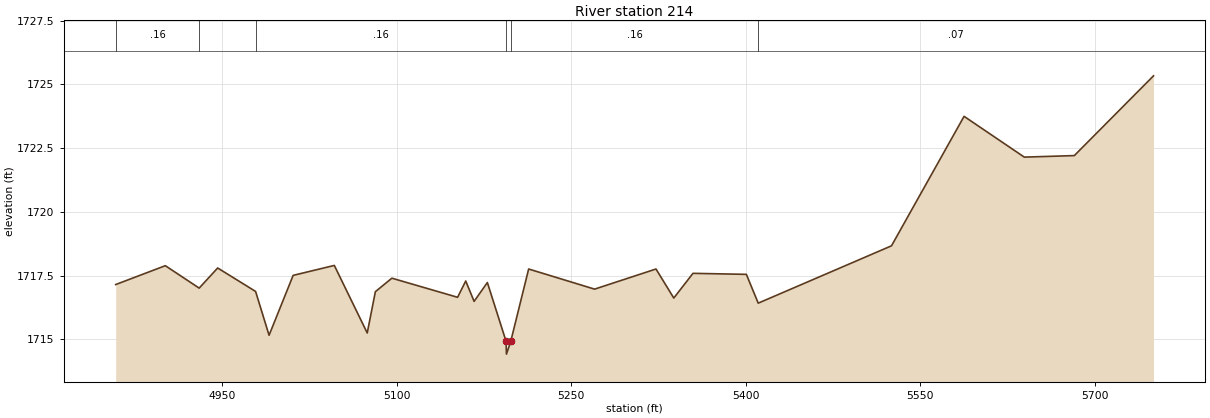
Type RM Length L Ch R = 1,214,0,0,0
BEGIN DESCRIPTION:
Elm 01 45 214.485
END DESCRIPTION:
XS GIS Cut Line= 4
      1561429.99      6850363.01      1561551.18      6850289.58
      1561677.20      6850167.29      1561864.70      6849623.62
#Sta/Elev= 30
  4858.3 1717.15  4901.0 1717.89  4930.1 1717.01  4946.0 1717.80  4978.6 1716.88
  4990.2 1715.16  5010.9 1717.51  5046.3 1717.90  5074.6 1715.25  5081.6 1716.87
  5095.8 1717.40  5152.3 1716.65  5159.3 1717.29  5166.5 1716.49  5177.9 1717.23
  5194.0 1714.92  5194.3 1714.42  5198.0 1714.92  5213.4 1717.76  5270.1 1716.97
  5322.9 1717.76  5338.2 1716.62  5354.7 1717.59  5400.6 1717.55  5410.8 1716.42
  5525.4 1718.67  5587.8 1723.75  5639.6 1722.15  5682.6 1722.21  5750.7 1725.34
#Mann=6,-1,0
  4858.3    0.16       0  4930.1    0.07       0  4978.6    0.16       0
  5194.0    0.07       0  5198.0    0.16       0  5410.8    0.07       0
Bank Sta=5194,5198
Exp/Cntr=0.3,0.1

Chan Stop Cuts=-1