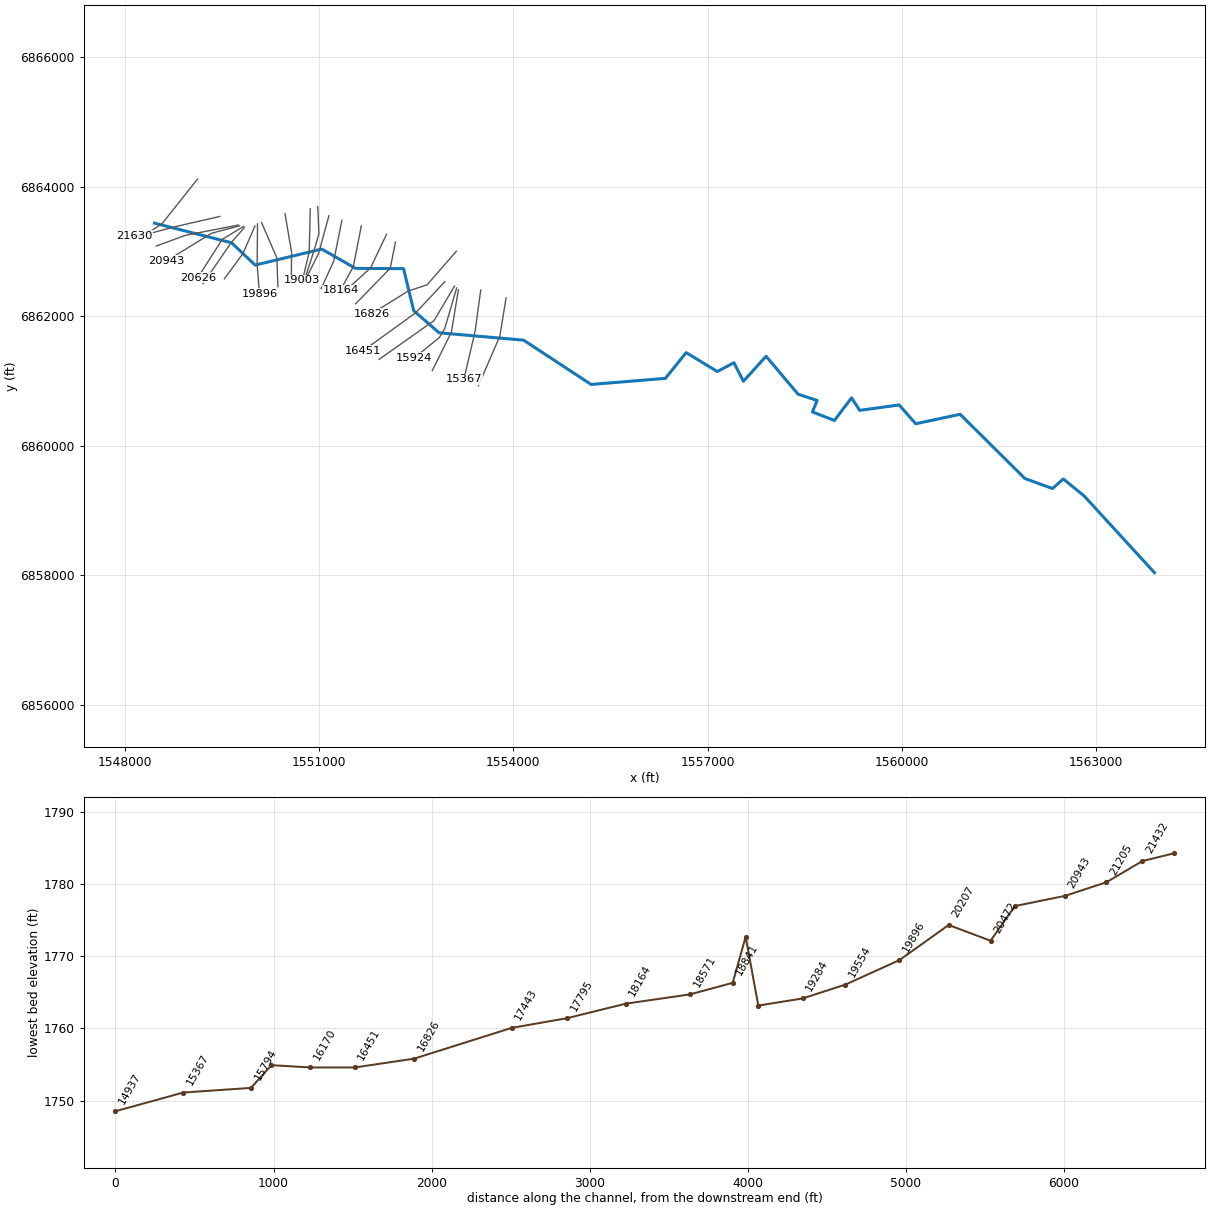
--- Elm 01 47.prj (project) ---

Proj Title=Elm 01 47 Base Level Engineering
Current Plan=p01
Default Exp/Contr=0.3,0.1
English Units
Geom File=g01
Flow File=f01
Plan File=p01
Y Axis Title=Elevation
X Axis Title(PF)=Main Channel Distance
X Axis Title(XS)=Station
BEGIN DESCRIPTION:
Elm 01 47
END DESCRIPTION:
DSS Export Rating Curves= 0
DSS Export Rating Curve Sorted= 0
DSS Export Volume Flow Curves= 0
DXF OffsetX= 0
DXF OffsetY= 0
DXF ScaleX= 1
DXF ScaleY= 10

--- Elm 01 47.p01 (plan) ---

Plan Title=Multiple Run
Program Version=4.10
Short Identifier=Multiple
Geom File=g01
Flow File=f01
Subcritical Flow
K Sum by GR= 0
Std Step Tol= 0.01
Critical Tol= 0.01
Num of Std Step Trials= 20
Max Error Tol= 0.3
Flow Tol Ratio= 0.001
Split Flow NTrial= 30
Split Flow Tol= 0.02
Split Flow Ratio= 0.02
Log Output Level= 0
Friction Slope Method= 1
Unsteady Friction Slope Method= 2
Unsteady Bridges Friction Slope Method= 1
Parabolic Critical Depth
Global Vel Dist= 1 , 1 , 1
Global Log Level= 0
CheckData=True
Encroach Param=-1 ,0,0, 0
BEGIN DESCRIPTION:
Multiple Run
END DESCRIPTION:
Computation Interval=1HOUR
Output Interval=1HOUR
Run HTab= 0
Run UNet= 0
Run PostProcess= 0
Run WQNet= 0
UNET Theta= 1
UNET Theta Warmup= 1
UNET ZTol= 0.02
UNET ZSATol= 0.05
UNET MxIter= 20
UNET MaxInSteps= 0
UNET DtIC= 0
UNET DtMin= 0
UNET MaxCRTS= 20
UNET WFStab= 2
UNET SFStab= 1
UNET WFX= 1
UNET SFX= 1
UNET DSS MLevel= 4
UNET DZMax Abort= 100
UNET Convert EG Bridges= 0
UNET Use Existing IB Tables=-1
UNET Froude Reduction=False
UNET Froude Limit= 1
UNET Froude Power= 10
UNET Time Slicing=0,0, 5
UNET Junction Losses=0
Instantaneous Interval=1HOUR
Write IC File= 0
Write IC File at Sim End=0
Echo Input=False
Echo Parameters=False
Echo Output=False
Write Detailed= 0
WQ AD Non Conservative
WQ ULTIMATE=-1
WQ Max Comp Step=1HOUR
WQ Output Interval=15MIN
WQ Output Selected Increments= 0
WQ Output face flow=0
WQ Output face velocity=0
WQ Output face area=0
WQ Output face dispersion=0
WQ Output cell volume=0
WQ Output cell surface area=0
WQ Output cell continuity=0
WQ Output cumulative cell continuity=0
WQ Output face conc=0
WQ Output face dconc_dx=0
WQ Output face courant=0
WQ Output face peclet=0
WQ Output face adv mass=0
WQ Output face disp mass=0
WQ Output cell mass=0
WQ Output cell source sink temp=0
WQ Output cell source sink nsm=0
WQ Output MaxMinRange=-1
WQ Daily Max Min Mean=-1
WQ Daily Range=0
WQ Daily Time=0
WQ Create Restart=0
WQ Fixed Restart=0
WQ System Summary=0
WQ Use Fixed Temperature=0
Sorting and Armoring Iterations= 10
XS Update Threshold= 0.02
Hydraulics Update Threshold= 0.02
Energy Slope Method= 1
Volume Change Method= 0
XS Weighting Method= 0
Number of US Weighted Cross Sections= 1
Number of DS Weighted Cross Sections= 1
Upstream XS Weight=0.25
Main XS Weight=0.5
Downstream XS Weight=0.25
Number of DS XS's Weighted with US Boundary= 1
Upstream Boundary Weight= 1
Weight of XSs Associated with US Boundary= 0
Number of US XS's Weighted with DS Boundary= 1
Downstream Boundary Weight= 0.5
Weight of XSs Associated with DS Boundary= 0.5
Sediment Output Level= 4
Mass or Volume Output= 0
Output Increment Type= 1
Profile and TS Output Increment= 10
XS Output Flag= 0
XS Output Increment= 10
Disregard all LS=0
Disregard all Conn=0
Disregard all Breaches=0
Disregard all Pumps=0

--- Elm 01 47.f01 (steady flow) ---

Flow Title=Multiple
Number of Profiles=7
Profile Names=10-year,25-year,50-year,1pct_min,100-year,1pct_plu,500-year
River Rch & RM= Elm 01 47,Reach-1,21630
     155     209     252     189     303     416     442
River Rch & RM= Elm 01 47,Reach-1,16826
     305     427     528     405     649     892     992
River Rch & RM= Elm 01 47,Reach-1,13966
     362     510     633     486     779    1070    1200
River Rch & RM= Elm 01 47,Reach-1,10114
     398     560     696     535     858    1180    1320
River Rch & RM= Elm 01 47,Reach-1,4582
     461     653     814     627    1010    1380    1560
Boundary for River Rch & Prof#=Elm 01 47,Reach-1,1
Up Type=0
Dn Type=3
Dn Slope=0.005
Boundary for River Rch & Prof#=Elm 01 47,Reach-1,2
Up Type=0
Dn Type=3
Dn Slope=0.005
Boundary for River Rch & Prof#=Elm 01 47,Reach-1,3
Up Type=0
Dn Type=3
Dn Slope=0.005
Boundary for River Rch & Prof#=Elm 01 47,Reach-1,4
Up Type=0
Dn Type=3
Dn Slope=0.005
Boundary for River Rch & Prof#=Elm 01 47,Reach-1,5
Up Type=0
Dn Type=3
Dn Slope=0.005
Boundary for River Rch & Prof#=Elm 01 47,Reach-1,6
Up Type=0
Dn Type=3
Dn Slope=0.005
Boundary for River Rch & Prof#=Elm 01 47,Reach-1,7
Up Type=0
Dn Type=3
Dn Slope=0.005

--- Elm 01 47.g01 (geometry) ---

Geom Title=Existing Conditions

River Reach=Elm 01 47,Reach-1
Reach XY= 30
      1548455.00      6863438.00      1549646.65      6863134.81
      1550010.67      6862789.98      1551039.84      6863037.61
      1551561.25      6862739.35      1552303.81      6862734.55
      1552460.46      6862085.55      1552852.70      6861743.83
      1554158.42      6861630.20      1555201.33      6860945.70
      1556348.97      6861039.61      1556670.03      6861437.67
      1557151.58      6861145.76      1557408.44      6861280.80
      1557554.80      6860994.98      1557904.65      6861380.79
      1558398.15      6860795.81      1558694.12      6860698.30
      1558621.02      6860520.86      1558961.15      6860389.74
      1559225.31      6860738.47      1559351.55      6860545.80
      1559962.02      6860628.99      1560215.69      6860338.53
      1560903.78      6860484.57      1561902.57      6859493.40
      1562330.08      6859337.37      1562496.46      6859485.42
      1562818.21      6859224.37      1563905.00      6858038.00

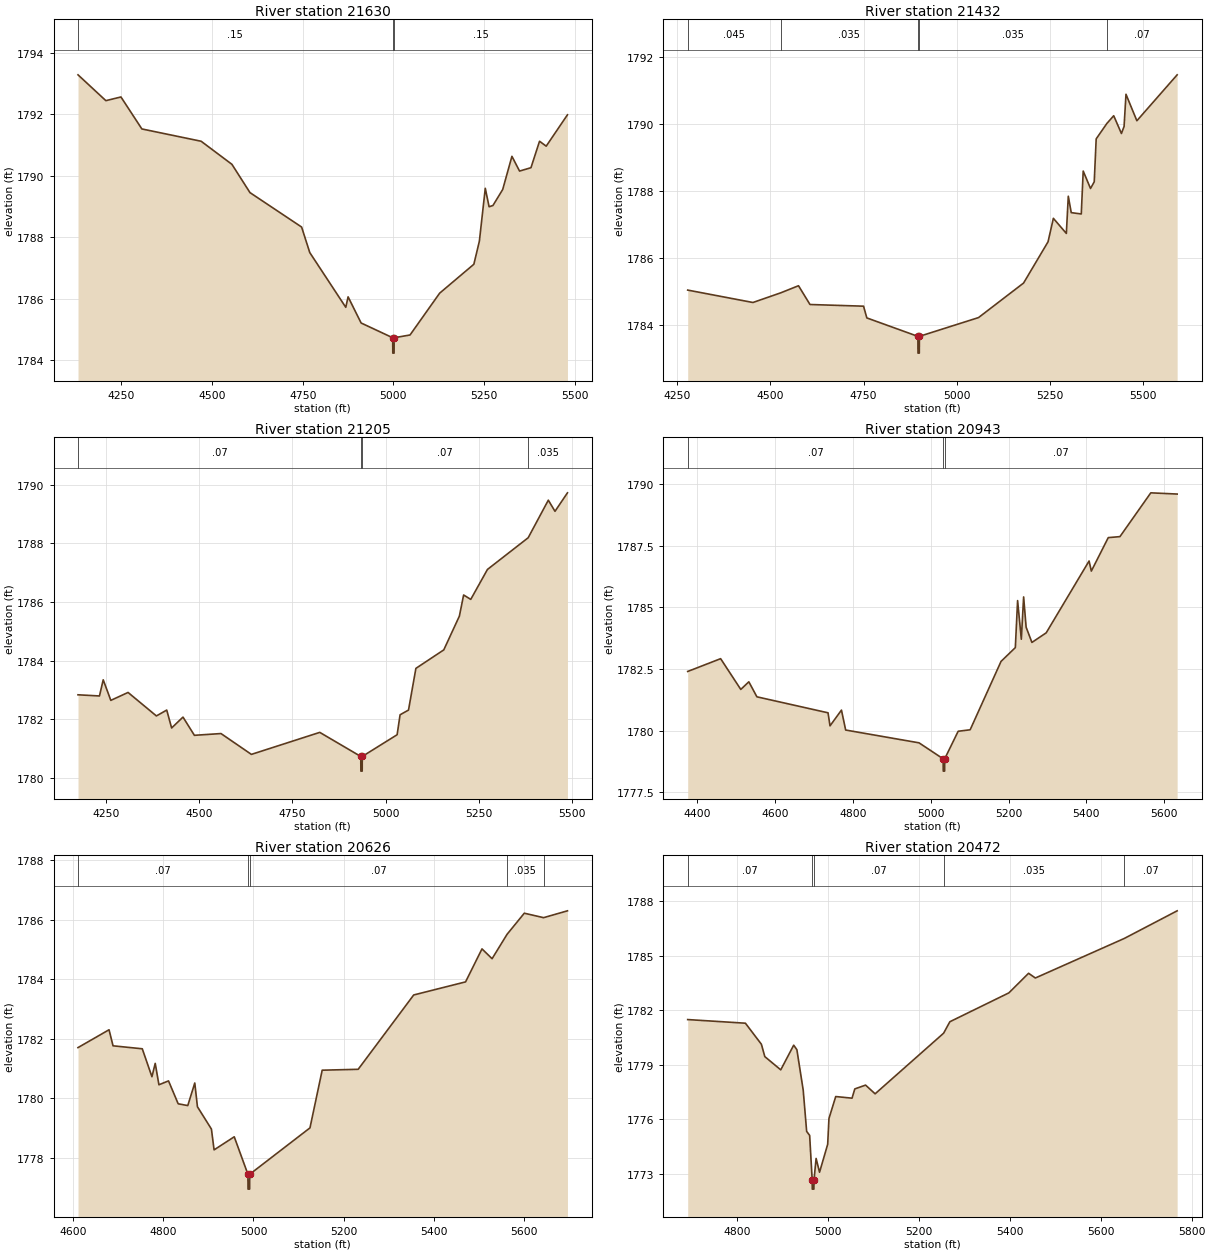
Type RM Length L Ch R = 1,21630,198,198,198
BEGIN DESCRIPTION:
Elm 01 47 50.0
END DESCRIPTION:
XS GIS Cut Line= 4
      1549120.93      6864119.21      1548571.79      6863428.27
      1548405.80      6863320.96      1548149.22      6863238.65
#Sta/Elev= 30
  4130.2 1793.28  4207.0 1792.44  4248.6 1792.56  4306.3 1791.52  4469.7 1791.12
  4554.6 1790.37  4604.4 1789.45  4746.8 1788.33  4769.3 1787.50  4868.6 1785.72
  4875.0 1786.06  4910.9 1785.21  4998.0 1784.73  4998.3 1784.23  5001.8 1784.23
  5002.0 1784.73  5045.8 1784.82  5127.5 1786.18  5221.8 1787.12  5237.0 1787.87
  5253.3 1789.59  5263.8 1788.99  5274.4 1789.03  5301.3 1789.55  5326.8 1790.63
  5347.8 1790.15  5379.3 1790.26  5402.9 1791.12  5421.3 1790.96  5479.9 1791.98
#Mann=3,-1,0
  4130.2    0.15       0  4998.0    0.05       0  5002.0    0.15       0
Bank Sta=4998,5002
Exp/Cntr=0.3,0.1

Type RM Length L Ch R = 1,21432,227,227,227
BEGIN DESCRIPTION:
Elm 01 47 21431.807
END DESCRIPTION:
XS GIS Cut Line= 3
      1549464.59      6863541.17      1548761.05      6863379.84
      1548190.69      6863226.55
#Sta/Elev= 30
  4278.2 1785.05  4453.1 1784.68  4528.1 1784.97  4575.3 1785.18  4606.1 1784.62
  4749.7 1784.57  4758.5 1784.22  4895.4 1783.67  4895.7 1783.17  4899.2 1783.17
  4899.4 1783.67  5058.0 1784.23  5178.8 1785.26  5244.4 1786.49  5258.7 1787.19
  5293.5 1786.74  5298.7 1787.85  5306.6 1787.36  5333.5 1787.32  5338.7 1788.60
  5358.3 1788.08  5368.3 1788.28  5373.5 1789.56  5402.2 1790.02  5420.5 1790.25
  5441.2 1789.72  5448.3 1789.93  5453.4 1790.89  5482.6 1790.10  5590.6 1791.47
#Mann=5,-1,0
  4278.2   0.045       0  4528.1   0.035       0  4895.4   0.035       0
  4899.4   0.035       0  5402.2    0.07       0
Bank Sta=4895.4,4899.4
Exp/Cntr=0.3,0.1

Type RM Length L Ch R = 1,21205,262,262,262
BEGIN DESCRIPTION:
Elm 01 47 21204.84
END DESCRIPTION:
XS GIS Cut Line= 3
      1549751.41      6863408.53      1548937.13      6863251.23
      1548483.69      6863084.66
#Sta/Elev= 30
  4175.2 1782.84  4232.7 1782.80  4242.8 1783.35  4263.2 1782.65  4309.4 1782.92
  4385.4 1782.12  4413.1 1782.32  4426.2 1781.71  4456.7 1782.08  4487.3 1781.46
  4558.6 1781.52  4640.1 1780.81  4823.4 1781.56  4933.4 1780.74  4933.7 1780.24
  4937.2 1780.24  4937.4 1780.74  5030.9 1781.48  5038.8 1782.16  5061.4 1782.32
  5081.2 1783.74  5156.0 1784.37  5197.8 1785.52  5209.2 1786.24  5228.3 1786.09
  5273.1 1787.11  5382.3 1788.19  5436.3 1789.47  5454.2 1789.09  5487.6 1789.72
#Mann=4,-1,0
  4175.2    0.07       0  4933.4    0.07       0  4937.4    0.07       0
  5382.3   0.035       0
Bank Sta=4933.4,4937.4
Exp/Cntr=0.3,0.1

Type RM Length L Ch R = 1,20943,317,317,317
BEGIN DESCRIPTION:
Elm 01 47 20943.45
END DESCRIPTION:
XS GIS Cut Line= 3
      1549766.79      6863396.19      1549338.09      6863282.07
      1548644.15      6862856.45
#Sta/Elev= 30
  4375.6 1782.40  4460.2 1782.92  4512.0 1781.67  4532.7 1781.98  4553.4 1781.37
  4736.2 1780.72  4741.3 1780.19  4770.7 1780.83  4781.5 1780.02  4970.0 1779.50
  5032.0 1778.85  5032.3 1778.35  5035.8 1778.35  5036.0 1778.85  5070.6 1779.97
  5101.4 1780.03  5180.8 1782.81  5217.5 1783.37  5223.3 1785.28  5232.9 1783.71
  5238.8 1785.43  5245.2 1784.20  5260.1 1783.58  5296.8 1783.97  5407.0 1786.89
  5412.8 1786.48  5456.3 1787.84  5486.3 1787.88  5565.6 1789.66  5633.3 1789.61
#Mann=3,-1,0
  4375.6    0.07       0  5032.0    0.07       0  5036.0    0.07       0
Bank Sta=5032,5036
Exp/Cntr=0.3,0.1

Type RM Length L Ch R = 1,20626,154,154,154
BEGIN DESCRIPTION:
Elm 01 47 20625.97
END DESCRIPTION:
XS GIS Cut Line= 3
      1549831.55      6863386.92      1549504.65      6863189.54
      1549125.25      6862597.31
#Sta/Elev= 30
  4611.0 1781.70  4679.8 1782.30  4688.7 1781.76  4753.5 1781.66  4774.9 1780.72
  4782.2 1781.17  4790.4 1780.45  4811.7 1780.58  4833.1 1779.81  4854.4 1779.75
  4869.9 1780.51  4875.8 1779.71  4906.8 1778.96  4912.7 1778.26  4957.4 1778.70
  4987.7 1777.44  4988.0 1776.94  4991.5 1776.94  4991.7 1777.44  5125.3 1779.00
  5152.4 1780.94  5232.2 1780.97  5355.3 1783.47  5470.3 1783.91  5506.7 1785.02
  5529.1 1784.69  5562.3 1785.51  5600.5 1786.22  5643.3 1786.07  5696.2 1786.30
#Mann=5,-1,0
  4611.0    0.07       0  4987.7    0.07       0  4991.7    0.07       0
  5562.3   0.035       0  5643.3    0.07       0
Bank Sta=4987.7,4991.7
Exp/Cntr=0.3,0.1

Type RM Length L Ch R = 1,20472,265,265,265
BEGIN DESCRIPTION:
Elm 01 47 20472.11
END DESCRIPTION:
XS GIS Cut Line= 3
      1549843.89      6863368.40      1549640.36      6863137.11
      1549205.89      6862502.35
#Sta/Elev= 30
  4690.8 1781.48  4817.8 1781.28  4853.0 1780.12  4860.5 1779.44  4895.6 1778.71
  4924.1 1780.07  4931.1 1779.82  4945.0 1777.60  4952.6 1775.32  4959.2 1775.10
  4964.8 1772.64  4965.0 1772.14  4968.5 1772.14  4968.8 1772.64  4973.4 1773.83
  4981.0 1773.07  4998.9 1774.61  5001.7 1776.03  5016.6 1777.24  5052.5 1777.15
  5058.6 1777.66  5082.3 1777.87  5103.3 1777.39  5254.1 1780.73  5267.8 1781.36
  5397.7 1782.95  5441.1 1784.03  5456.0 1783.77  5651.9 1785.95  5768.1 1787.47
#Mann=5,-1,0
  4690.8    0.07       0  4964.8    0.07       0  4968.8    0.07       0
  5254.1   0.035       0  5651.9    0.07       0
Bank Sta=4964.8,4968.8
Exp/Cntr=0.3,0.1

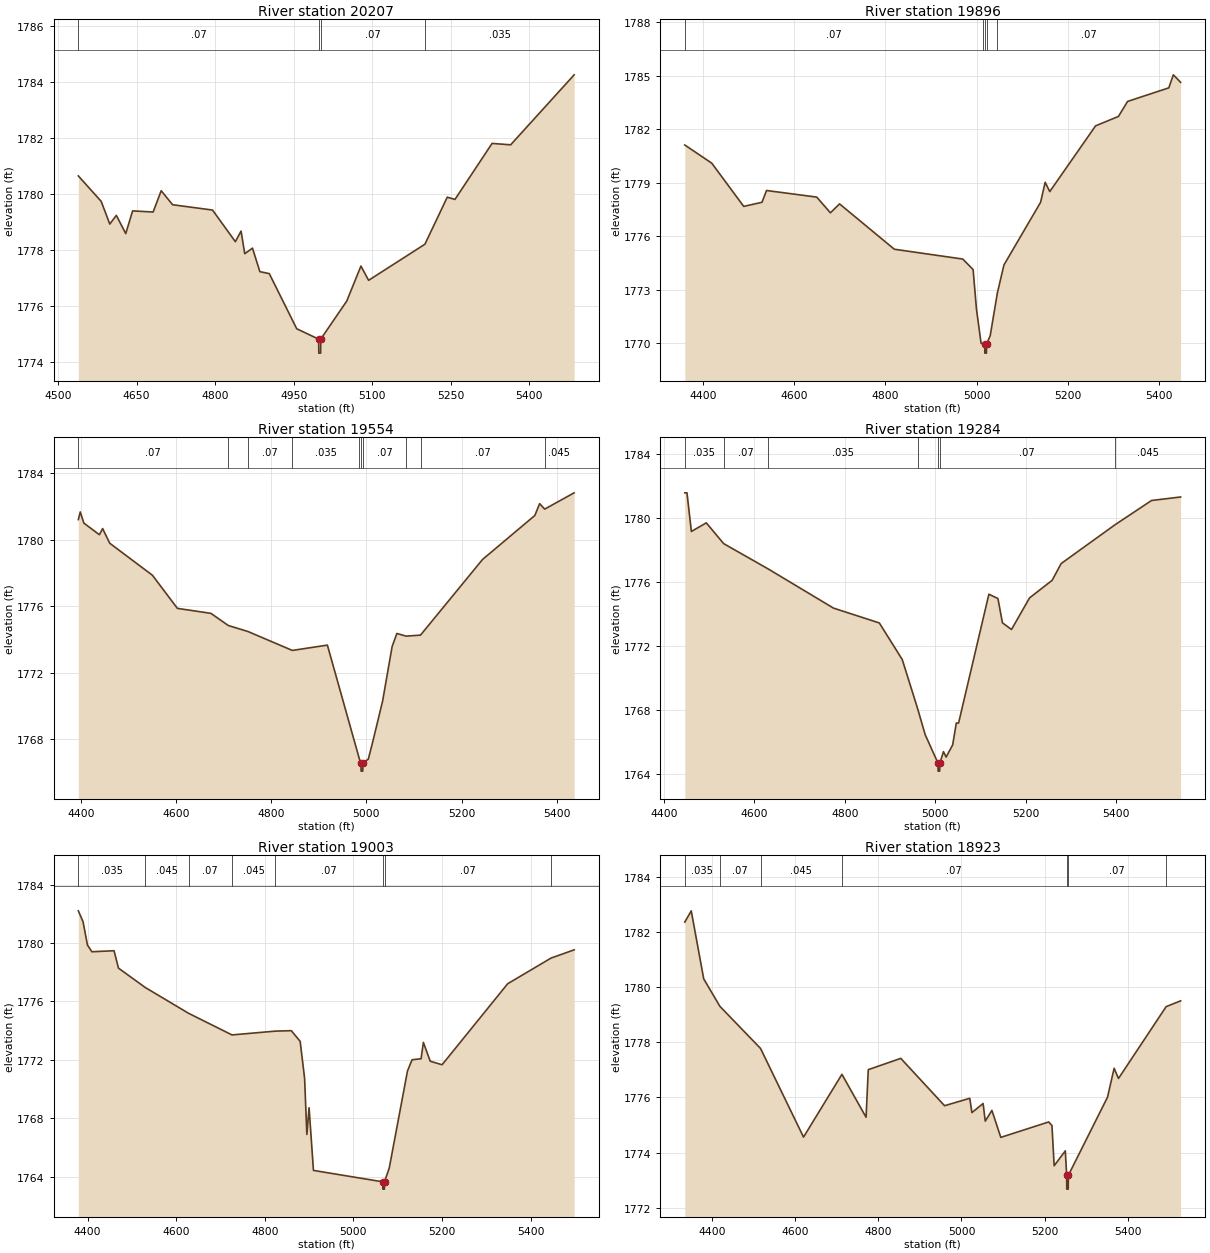
Type RM Length L Ch R = 1,20207,311,311,311
BEGIN DESCRIPTION:
Elm 01 47 20206.91
END DESCRIPTION:
XS GIS Cut Line= 3
      1550007.40      6863393.13      1549822.33      6862967.47
      1549535.47      6862578.82
#Sta/Elev= 30
  4538.7 1780.65  4582.4 1779.74  4598.8 1778.93  4611.3 1779.24  4629.3 1778.59
  4642.4 1779.40  4681.6 1779.36  4697.0 1780.12  4718.8 1779.62  4795.1 1779.43
  4838.7 1778.30  4849.6 1778.68  4856.6 1777.87  4871.4 1778.07  4885.5 1777.23
  4903.5 1777.16  4955.9 1775.19  4997.8 1774.82  4998.1 1774.32  5001.6 1774.32
  5001.8 1774.82  5051.5 1776.18  5078.6 1777.43  5093.2 1776.92  5200.8 1778.21
  5243.5 1779.89  5258.2 1779.81  5329.1 1781.81  5364.6 1781.76  5485.9 1784.26
#Mann=4,-1,0
  4538.7    0.07       0  4997.8    0.07       0  5001.8    0.07       0
  5200.8   0.035       0
Bank Sta=4997.8,5001.8
Exp/Cntr=0.3,0.1

Type RM Length L Ch R = 1,19896,342,342,342
BEGIN DESCRIPTION:
Elm 01 47 19895.7
END DESCRIPTION:
XS GIS Cut Line= 3
      1550047.49      6863427.07      1550041.32      6862797.83
      1550078.26      6862342.20
#Sta/Elev= 30
  4360.4 1781.12  4419.5 1780.10  4489.5 1777.68  4529.5 1777.91  4539.5 1778.57
  4649.5 1778.20  4679.5 1777.32  4699.5 1777.82  4819.5 1775.28  4969.5 1774.73
  4992.1 1774.14  4999.5 1771.92  5009.6 1770.01  5014.5 1769.98  5017.6 1769.96
  5017.8 1769.46  5021.3 1769.46  5021.6 1769.96  5029.6 1770.44  5045.2 1772.82
  5059.7 1774.40  5140.0 1777.91  5150.0 1779.03  5160.1 1778.51  5260.4 1782.19
  5310.6 1782.72  5330.6 1783.56  5420.9 1784.32  5430.9 1785.05  5446.8 1784.63
#Mann=5,-1,0
  4360.4    0.07       0  5014.5   0.035       0  5017.6    0.07       0
  5021.6   0.035       0  5045.2    0.07       0
Bank Sta=5017.6,5021.6
Exp/Cntr=0.3,0.1

Type RM Length L Ch R = 1,19554,270,270,270
BEGIN DESCRIPTION:
Elm 01 47 19554.05
END DESCRIPTION:
XS GIS Cut Line= 3
      1550109.18      6863448.62      1550346.67      6862899.61
      1550362.09      6862455.45
#Sta/Elev= 30
  4394.2 1781.20  4398.3 1781.66  4405.8 1780.99  4438.5 1780.29  4445.3 1780.66
  4460.2 1779.78  4550.1 1777.85  4602.5 1775.86  4673.0 1775.56  4709.5 1774.83
  4750.7 1774.47  4844.2 1773.33  4917.9 1773.65  4985.1 1766.81  4988.5 1766.57
  4988.8 1766.07  4992.3 1766.07  4992.5 1766.57  5004.0 1766.79  5014.0 1767.92
  5034.0 1770.28  5054.0 1773.56  5064.0 1774.35  5083.5 1774.19  5113.7 1774.25
  5244.1 1778.80  5354.2 1781.45  5364.2 1782.16  5374.8 1781.83  5436.8 1782.81
#Mann=10,-1,0
  4394.2    0.07       0  4709.5   0.035       0  4750.7    0.07       0
  4844.2   0.035       0  4985.1    0.07       0  4988.5    0.07       0
  4992.5    0.07       0  5083.5   0.035       0  5113.7    0.07       0
  5374.8   0.045       0
Bank Sta=4988.5,4992.5
Exp/Cntr=0.3,0.1

Type RM Length L Ch R = 1,19284,281,281,281
BEGIN DESCRIPTION:
Elm 01 47 19389.2
END DESCRIPTION:
XS GIS Cut Line= 3
      1550472.40      6863582.42      1550574.19      6862987.12
      1550568.03      6862493.60
#Sta/Elev= 30
  4445.8 1781.58  4450.6 1781.58  4460.4 1779.16  4493.4 1779.70  4531.8 1778.40
  4630.6 1776.81  4774.9 1774.36  4876.4 1773.43  4927.1 1771.14  4961.0 1768.08
  4977.8 1766.44  5006.3 1764.65  5006.5 1764.15  5010.0 1764.15  5010.3 1764.65
  5018.4 1765.37  5024.2 1765.03  5038.7 1765.79  5046.8 1767.16  5051.8 1767.16
  5118.9 1775.23  5138.9 1774.96  5148.9 1773.44  5168.9 1773.02  5208.9 1775.00
  5258.9 1776.10  5278.9 1777.15  5397.1 1779.56  5478.9 1781.10  5543.3 1781.32
#Mann=7,-1,0
  4445.8   0.035       0  4531.8    0.07       0  4630.6   0.035       0
  4961.0    0.07       0  5006.3    0.07       0  5010.3    0.07       0
  5397.1   0.045       0
Bank Sta=5006.3,5010.3
Exp/Cntr=0.3,0.1

Type RM Length L Ch R = 1,19003,80,80,80
BEGIN DESCRIPTION:
Elm 01 47 19196.2
END DESCRIPTION:
XS GIS Cut Line= 3
      1550863.17      6863658.58      1550846.19      6862993.94
      1550741.66      6862551.88
#Sta/Elev= 30
  4379.2 1782.20  4389.8 1781.46  4399.8 1779.86  4409.8 1779.40  4459.8 1779.47
  4469.8 1778.28  4530.0 1776.96  4628.0 1775.19  4726.0 1773.71  4824.0 1773.97
  4859.9 1774.00  4879.9 1773.27  4889.9 1770.74  4895.0 1766.90  4900.0 1768.73
  4909.9 1764.44  5066.3 1763.66  5066.5 1763.16  5070.0 1763.16  5070.3 1763.66
  5081.0 1764.61  5122.1 1771.24  5132.4 1772.01  5152.8 1772.08  5158.0 1773.20
  5173.5 1771.91  5200.2 1771.67  5348.2 1777.21  5446.3 1778.97  5498.3 1779.53
#Mann=8,-1,0
  4379.2   0.035       0  4530.0   0.045       0  4628.0    0.07       0
  4726.0   0.045       0  4824.0    0.07       0  5066.3    0.07       0
  5070.3    0.07       0  5446.3   0.045       0
Bank Sta=5066.3,5070.3
Exp/Cntr=0.3,0.1

Type RM Length L Ch R = 1,18923,82,82,82
BEGIN DESCRIPTION:
Elm 01 47 18922.67
END DESCRIPTION:
XS GIS Cut Line= 4
      1550978.57      6863693.47      1550995.71      6863273.12
      1550929.61      6863044.58      1550766.15      6862535.69
#Sta/Elev= 30
  4334.3 1782.37  4349.8 1782.78  4379.8 1780.31  4418.8 1779.31  4516.6 1777.78
  4620.0 1774.56  4712.4 1776.84  4770.5 1775.28  4775.8 1777.01  4854.0 1777.42
  4959.4 1775.70  5020.0 1775.97  5025.2 1775.45  5052.1 1775.78  5057.3 1775.14
  5073.3 1775.53  5094.7 1774.55  5209.9 1775.11  5217.8 1774.98  5223.1 1773.52
  5249.9 1774.06  5253.2 1773.17  5253.4 1772.67  5256.9 1772.67  5257.2 1773.17
  5351.5 1776.01  5367.4 1777.06  5377.9 1776.69  5492.6 1779.30  5527.4 1779.51
#Mann=7,-1,0
  4334.3   0.035       0  4418.8    0.07       0  4516.6   0.045       0
  4712.4    0.07       0  5253.2    0.07       0  5257.2    0.07       0
  5492.6   0.045       0
Bank Sta=5253.2,5257.2
Exp/Cntr=0.3,0.1

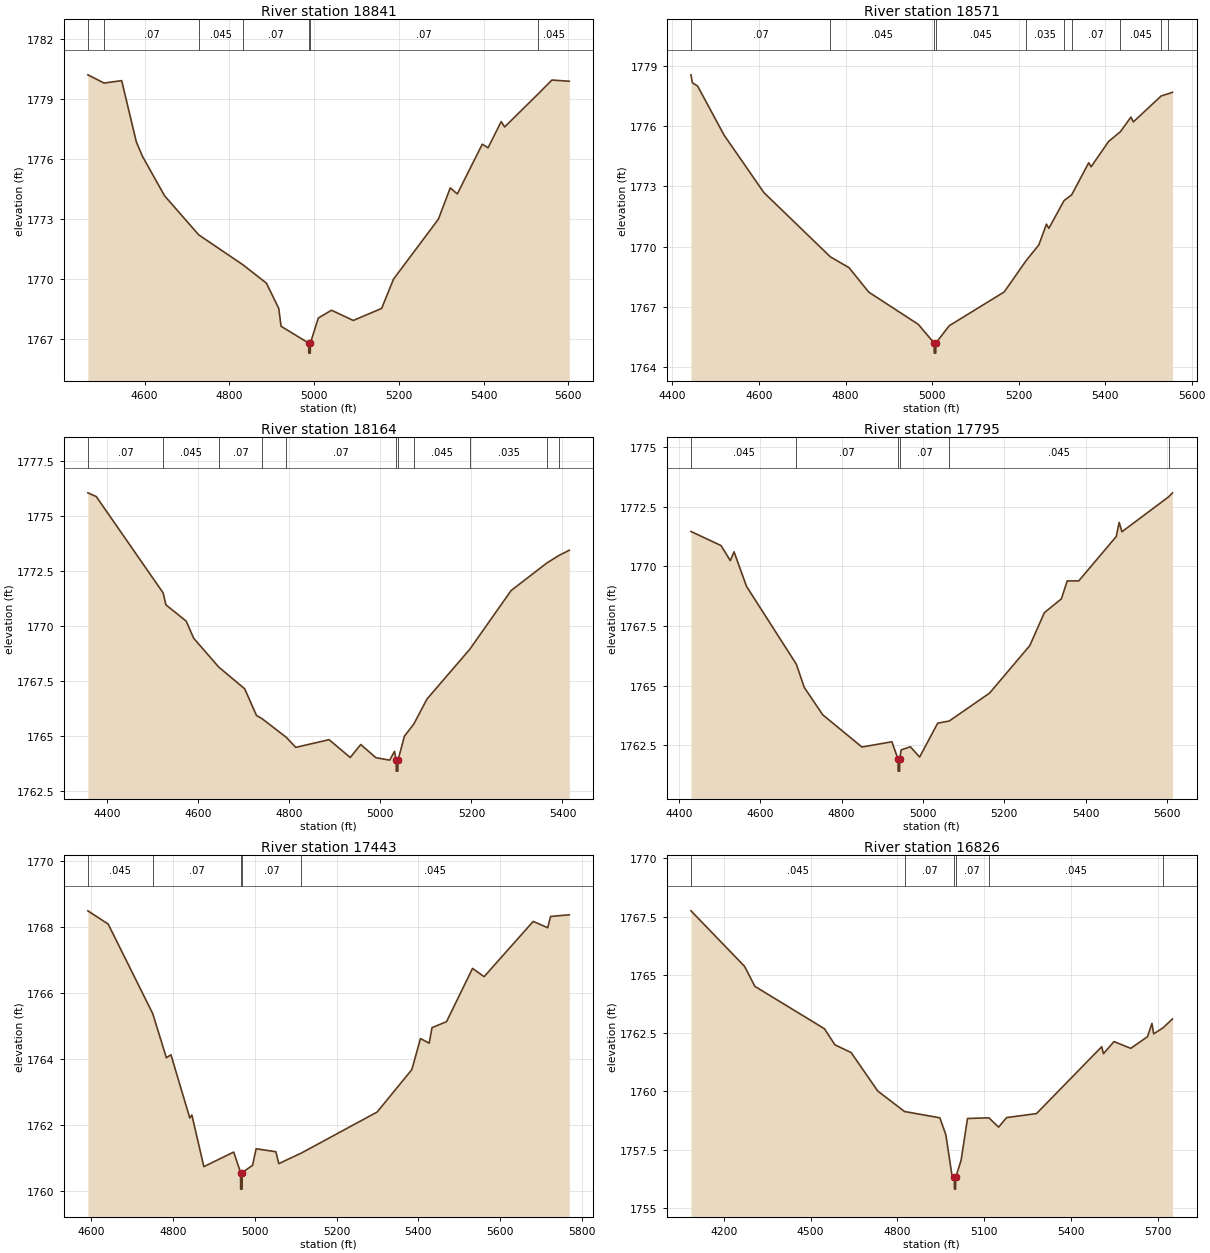
Type RM Length L Ch R = 1,18841,270,270,270
BEGIN DESCRIPTION:
Elm 01 47 18690.45
END DESCRIPTION:
XS GIS Cut Line= 3
      1551150.37      6863552.44      1550989.98      6862966.41
      1550752.48      6862494.49
#Sta/Elev= 30
  4466.3 1780.19  4504.6 1779.78  4546.1 1779.90  4580.6 1776.85  4595.3 1776.12
  4647.2 1774.16  4727.8 1772.21  4832.6 1770.71  4887.6 1769.80  4916.7 1768.54
  4922.1 1767.65  4987.3 1766.81  4987.5 1766.31  4991.0 1766.31  4991.3 1766.81
  5010.0 1768.06  5041.1 1768.45  5092.5 1767.94  5159.4 1768.54  5187.4 1770.00
  5293.3 1772.99  5321.3 1774.55  5338.0 1774.25  5396.8 1776.73  5410.5 1776.55
  5441.5 1777.86  5449.6 1777.59  5527.8 1779.22  5561.2 1779.93  5602.2 1779.87
#Mann=7,-1,0
  4466.3   0.045       0  4504.6    0.07       0  4727.8   0.045       0
  4832.6    0.07       0  4987.3    0.07       0  4991.3    0.07       0
  5527.8   0.045       0
Bank Sta=4987.3,4991.3
Exp/Cntr=0.3,0.1

Type RM Length L Ch R = 1,18571,407,407,407
BEGIN DESCRIPTION:
Elm 01 47 18444.78
END DESCRIPTION:
XS GIS Cut Line= 3
      1551351.19      6863483.14      1551224.73      6862850.85
      1551030.42      6862425.22
#Sta/Elev= 30
  4442.9 1778.54  4446.0 1778.15  4458.3 1777.98  4519.5 1775.54  4611.3 1772.69
  4765.3 1769.49  4808.0 1768.96  4853.9 1767.74  4968.2 1766.14  5004.9 1765.21
  5005.1 1764.71  5008.6 1764.71  5008.9 1765.21  5039.6 1766.07  5166.8 1767.75
  5217.2 1769.30  5246.9 1770.09  5264.4 1771.12  5269.9 1770.91  5305.1 1772.29
  5322.8 1772.58  5362.1 1774.17  5367.6 1773.97  5408.1 1775.23  5435.2 1775.71
  5459.7 1776.44  5465.2 1776.20  5529.6 1777.49  5544.2 1777.59  5555.6 1777.67
#Mann=10,-1,0
  4442.9    0.07       0  4765.3   0.045       0  5004.9   0.045       0
  5008.9   0.045       0  5217.2   0.035       0  5305.1   0.045       0
  5322.8    0.07       0  5435.2   0.045       0  5529.6    0.07       0
  5544.2   0.045       0
Bank Sta=5004.9,5008.9
Exp/Cntr=0.3,0.1

Type RM Length L Ch R = 1,18164,369,369,369
BEGIN DESCRIPTION:
Elm 01 47 18164.18
END DESCRIPTION:
XS GIS Cut Line= 3
      1551651.34      6863396.15      1551527.98      6862766.99
      1551328.34      6862401.50
#Sta/Elev= 30
  4357.5 1776.07  4376.0 1775.90  4522.9 1771.52  4528.9 1770.98  4573.5 1770.24
  4590.0 1769.46  4645.0 1768.15  4702.1 1767.16  4727.9 1765.95  4739.8 1765.81
  4793.2 1764.96  4814.2 1764.50  4887.4 1764.85  4933.8 1764.04  4956.9 1764.63
  4990.3 1764.03  5020.6 1763.92  5031.1 1764.32  5034.8 1763.92  5035.0 1763.42
  5038.5 1763.42  5038.8 1763.92  5052.9 1765.01  5073.8 1765.57  5102.2 1766.69
  5196.5 1768.96  5287.3 1771.63  5366.4 1772.89  5392.9 1773.23  5415.1 1773.46
#Mann=11,-1,0
  4357.5    0.07       0  4522.9   0.045       0  4645.0    0.07       0
  4739.8   0.045       0  4793.2    0.07       0  5034.8    0.07       0
  5038.8    0.07       0  5073.8   0.045       0  5196.5   0.035       0
  5366.4   0.045       0  5392.9    0.07       0
Bank Sta=5034.8,5038.8
Exp/Cntr=0.3,0.1

Type RM Length L Ch R = 1,17795,352,352,352
BEGIN DESCRIPTION:
Elm 01 47 17795.07
END DESCRIPTION:
XS GIS Cut Line= 3
      1552039.97      6863263.56      1551793.23      6862745.40
      1551342.89      6862335.15
#Sta/Elev= 30
  4430.1 1771.46  4504.0 1770.87  4526.7 1770.24  4535.9 1770.61  4566.6 1769.16
  4689.0 1765.90  4708.4 1764.93  4753.8 1763.78  4850.2 1762.43  4923.8 1762.65
  4939.0 1761.92  4939.2 1761.42  4942.7 1761.42  4943.0 1761.92  4946.5 1762.31
  4969.2 1762.44  4991.9 1762.01  5036.4 1763.43  5064.7 1763.52  5163.9 1764.69
  5262.7 1766.68  5298.5 1768.06  5340.4 1768.64  5354.6 1769.39  5383.0 1769.39
  5475.1 1771.25  5482.3 1771.84  5489.1 1771.45  5603.7 1772.91  5613.2 1773.08
#Mann=6,-1,0
  4430.1   0.045       0  4689.0    0.07       0  4939.0    0.07       0
  4943.0    0.07       0  5064.7   0.045       0  5603.7    0.07       0
Bank Sta=4939,4943
Exp/Cntr=0.3,0.1

Type RM Length L Ch R = 1,17443,617,617,617
BEGIN DESCRIPTION:
Elm 01 47 17442.61
END DESCRIPTION:
XS GIS Cut Line= 3
      1552178.76      6863146.31      1552098.58      6862742.31
      1551564.97      6862193.28
#Sta/Elev= 30
  4591.9 1768.48  4641.6 1768.08  4750.7 1765.37  4783.9 1764.04  4795.1 1764.13
  4841.2 1762.22  4846.3 1762.31  4875.6 1760.75  4948.6 1761.19  4965.4 1760.57
  4965.6 1760.07  4969.1 1760.07  4969.4 1760.57  4994.7 1760.79  5003.4 1761.29
  5051.7 1761.20  5058.9 1760.84  5114.0 1761.16  5299.4 1762.40  5384.2 1763.68
  5405.4 1764.62  5426.7 1764.48  5433.6 1764.95  5469.1 1765.13  5532.7 1766.74
  5561.0 1766.49  5681.1 1768.16  5716.6 1767.97  5723.6 1768.31  5769.4 1768.36
#Mann=5,-1,0
  4591.9   0.045       0  4750.7    0.07       0  4965.4    0.07       0
  4969.4    0.07       0  5114.0   0.045       0
Bank Sta=4965.4,4969.4
Exp/Cntr=0.3,0.1

Type RM Length L Ch R = 1,16826,375,375,375
BEGIN DESCRIPTION:
Elm 01 47 16842.07
END DESCRIPTION:
XS GIS Cut Line= 4
      1553120.01      6863004.41      1552667.06      6862484.82
      1552374.75      6862388.78      1551808.32      6862036.55
#Sta/Elev= 30
  4086.5 1767.75  4271.6 1765.37  4307.3 1764.51  4547.9 1762.69  4584.0 1762.00
  4640.0 1761.67  4732.0 1760.02  4824.5 1759.14  4946.7 1758.87  4967.4 1758.14
  4988.5 1756.40  4996.8 1756.31  4997.1 1755.81  5000.9 1755.81  5001.2 1756.31
  5020.1 1757.05  5042.2 1758.84  5116.1 1758.87  5149.6 1758.47  5177.4 1758.88
  5280.6 1759.05  5506.1 1761.92  5512.0 1761.62  5548.6 1762.14  5606.5 1761.85
  5664.3 1762.35  5679.7 1762.92  5685.6 1762.47  5718.0 1762.73  5750.5 1763.11
#Mann=6,-1,0
  4086.5   0.045       0  4824.5    0.07       0  4996.8    0.07       0
  5001.2    0.07       0  5116.1   0.045       0  5718.0    0.07       0
Bank Sta=4996.8,5001.2
Exp/Cntr=0.3,0.1

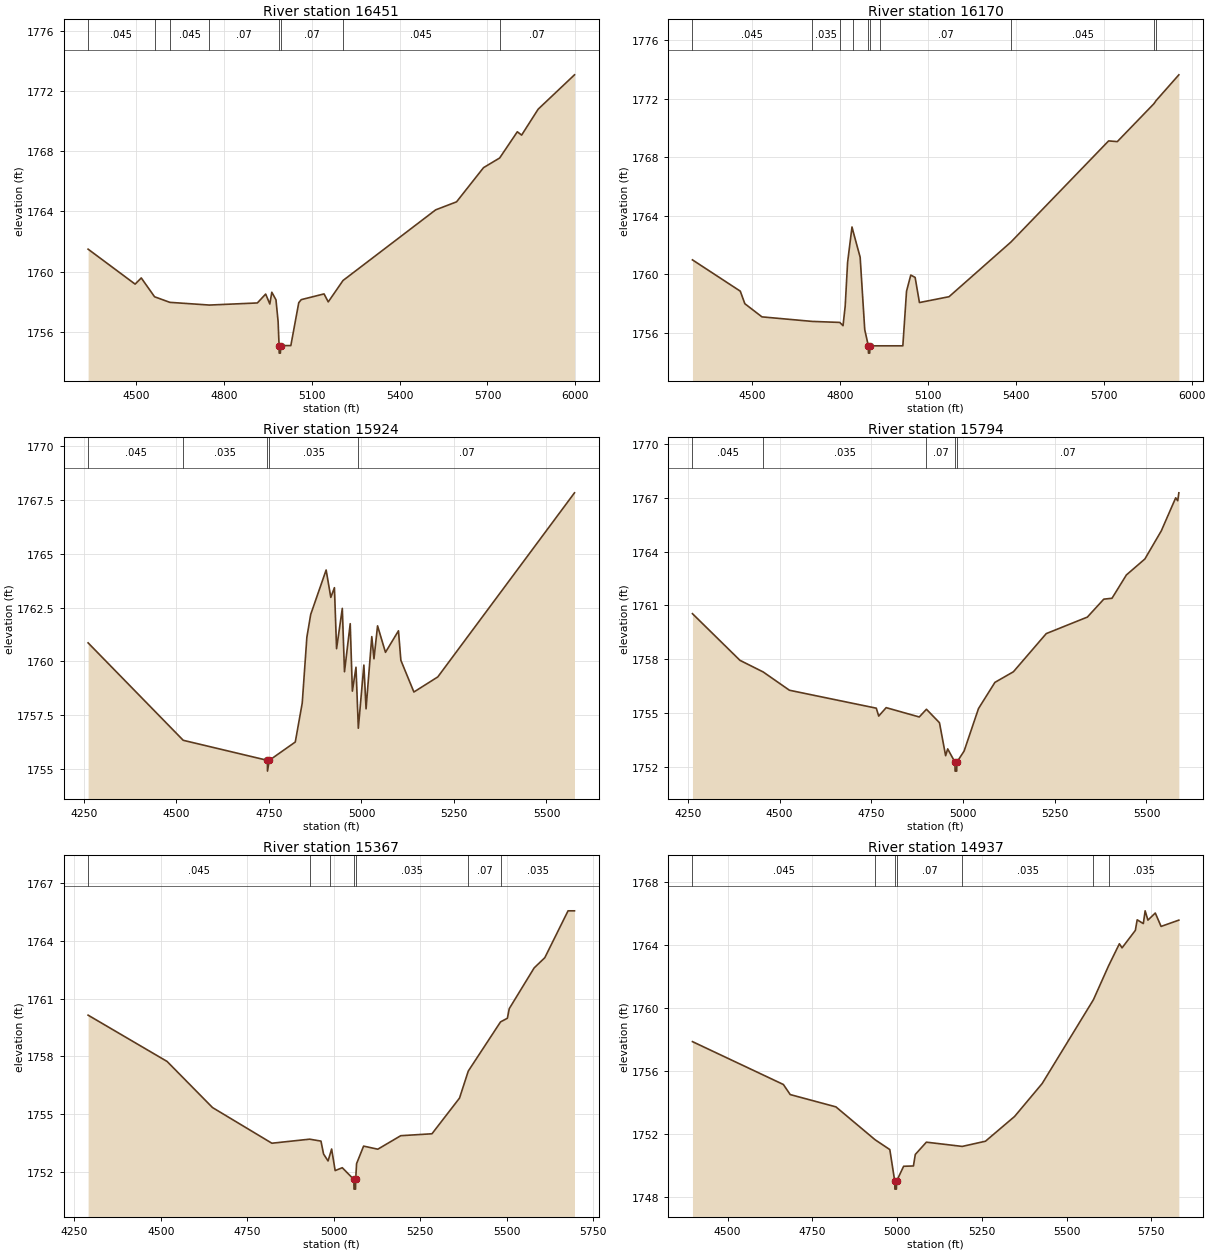
Type RM Length L Ch R = 1,16451,281,281,281
BEGIN DESCRIPTION:
Elm 01 47 16451.2
END DESCRIPTION:
XS GIS Cut Line= 3
      1552943.72      6862535.69      1552493.38      6862054.50
      1551682.18      6861468.46
#Sta/Elev= 30
  4337.1 1761.49  4497.5 1759.17  4518.5 1759.58  4563.9 1758.33  4616.1 1757.96
  4751.0 1757.78  4914.7 1757.92  4943.0 1758.51  4957.2 1757.85  4964.0 1758.63
  4978.2 1758.13  4985.5 1756.68  4988.8 1755.09  4989.2 1754.59  4993.4 1754.59
  4993.8 1755.09  5028.9 1755.09  5056.0 1757.94  5064.5 1758.14  5142.2 1758.52
  5156.6 1757.99  5207.0 1759.41  5523.3 1764.10  5594.4 1764.63  5686.5 1766.90
  5741.5 1767.54  5801.8 1769.28  5816.5 1769.06  5872.9 1770.78  5996.9 1773.06
#Mann=8,-1,0
  4337.1   0.045       0  4563.9    0.07       0  4616.1   0.045       0
  4751.0    0.07       0  4988.8    0.07       0  4993.8    0.07       0
  5207.0   0.045       0  5741.5    0.07       0
Bank Sta=4988.8,4993.8
Exp/Cntr=0.3,0.1

Type RM Length L Ch R = 1,16170,246,246,246
BEGIN DESCRIPTION:
Elm 01 47 16273.2
END DESCRIPTION:
XS GIS Cut Line= 3
      1553091.92      6862465.62      1552774.25      6861932.05
      1551926.05      6861333.68
#Sta/Elev= 30
  4297.4 1760.97  4460.5 1758.83  4476.1 1757.97  4534.5 1757.07  4705.8 1756.76
  4799.8 1756.69  4811.0 1756.47  4818.3 1757.79  4826.6 1760.81  4841.6 1763.22
  4845.8 1762.89  4869.4 1761.15  4885.0 1756.20  4897.3 1755.09  4897.7 1754.59
  4902.0 1754.59  4902.3 1755.09  4938.4 1755.09  5015.0 1755.09  5027.6 1758.83
  5042.1 1759.93  5056.9 1759.77  5071.6 1758.05  5172.6 1758.45  5383.7 1762.19
  5716.9 1769.11  5746.5 1769.06  5871.7 1771.66  5878.5 1771.86  5956.4 1773.63
#Mann=10,-1,0
  4297.4   0.045       0  4705.8   0.035       0  4799.8    0.07       0
  4845.8   0.035       0  4897.3    0.07       0  4902.3   0.035       0
  4938.4    0.07       0  5383.7   0.045       0  5871.7    0.07       0
  5878.5   0.045       0
Bank Sta=4897.3,4902.3
Exp/Cntr=0.3,0.1

Type RM Length L Ch R = 1,15924,130,130,130
BEGIN DESCRIPTION:
Elm 01 47 15923.77
END DESCRIPTION:
XS GIS Cut Line= 4
      1553123.90      6862435.37      1552940.61      6861810.84
      1552857.33      6861672.04      1552469.43      6861353.45
#Sta/Elev= 30
  4261.1 1760.86  4518.2 1756.34  4745.7 1755.41  4746.0 1754.91  4750.7 1755.41
  4821.1 1756.26  4839.9 1758.07  4852.4 1761.12  4862.8 1762.18  4904.5 1764.24
  4917.1 1762.97  4926.9 1763.42  4932.7 1760.59  4948.2 1762.46  4954.1 1759.52
  4969.6 1761.75  4975.4 1758.62  4985.2 1759.73  4991.5 1756.90  5006.5 1759.83
  5012.4 1757.80  5027.9 1761.15  5033.8 1760.12  5043.5 1761.65  5064.9 1760.42
  5100.0 1761.42  5106.5 1760.05  5141.7 1758.58  5206.3 1759.28  5575.8 1767.82
#Mann=5,-1,0
  4261.1   0.045       0  4518.2   0.035       0  4745.7    0.07       0
  4750.7   0.035       0  4991.5    0.07       0
Bank Sta=4745.7,4750.7
Exp/Cntr=0.3,0.1

Type RM Length L Ch R = 1,15794,427,427,427
BEGIN DESCRIPTION:
Elm 01 47 15569.44
END DESCRIPTION:
XS GIS Cut Line= 3
      1553151.36      6862408.91      1553043.40      6861754.99
      1552748.11      6861161.34
#Sta/Elev= 30
  4262.4 1760.54  4391.8 1757.94  4455.2 1757.29  4526.8 1756.27  4763.5 1755.27
  4770.1 1754.83  4790.4 1755.30  4880.6 1754.78  4900.2 1755.21  4935.7 1754.46
  4952.5 1752.62  4958.1 1753.00  4977.9 1752.26  4978.3 1751.76  4982.7 1751.76
  4983.1 1752.26  5002.9 1752.88  5042.1 1755.25  5086.9 1756.71  5137.2 1757.30
  5226.8 1759.43  5338.8 1760.35  5383.6 1761.35  5406.0 1761.40  5445.2 1762.70
  5495.6 1763.59  5540.4 1765.16  5579.6 1767.00  5585.2 1766.84  5588.2 1767.28
#Mann=5,-1,0
  4262.4   0.045       0  4455.2   0.035       0  4900.2    0.07       0
  4977.9    0.07       0  4983.1    0.07       0
Bank Sta=4977.9,4983.1
Exp/Cntr=0.3,0.1

Type RM Length L Ch R = 1,15367,430,430,430
BEGIN DESCRIPTION:
Elm 01 47 15218.61
END DESCRIPTION:
XS GIS Cut Line= 3
      1553496.39      6862404.21      1553409.76      6861770.18
      1553235.87      6861024.40
#Sta/Elev= 30
  4289.9 1760.14  4518.2 1757.74  4649.4 1755.35  4821.0 1753.50  4930.1 1753.71
  4962.9 1753.61  4970.4 1752.94  4983.4 1752.58  4990.1 1752.98  4993.7 1753.20
  5003.9 1752.08  5024.5 1752.23  5058.0 1751.62  5058.4 1751.12  5062.8 1751.12
  5063.2 1751.62  5065.8 1752.44  5086.1 1753.35  5127.2 1753.19  5193.4 1753.89
  5283.7 1753.99  5363.3 1755.84  5388.6 1757.24  5481.8 1759.79  5501.6 1759.98
  5507.1 1760.48  5579.0 1762.59  5609.8 1763.12  5677.0 1765.55  5695.6 1765.55
#Mann=7,-1,0
  4289.9   0.045       0  4930.1    0.07       0  4990.1   0.035       0
  5058.0   0.035       0  5063.2   0.035       0  5388.6    0.07       0
  5481.8   0.035       0
Bank Sta=5058,5063.2
Exp/Cntr=0.3,0.1

Type RM Length L Ch R = 1,14937,433,433,433
BEGIN DESCRIPTION:
Elm 01 47 14937.13
END DESCRIPTION:
XS GIS Cut Line= 3
      1553887.49      6862282.70      1553791.88      6861693.63
      1553459.50      6860924.24
#Sta/Elev= 30
  4396.4 1757.89  4664.6 1755.17  4684.8 1754.53  4819.6 1753.75  4935.4 1751.66
  4978.6 1751.04  4993.2 1749.03  4993.6 1748.53  4998.1 1748.53  4998.5 1749.03
  5019.4 1749.98  5048.3 1750.00  5053.8 1750.73  5086.5 1751.51  5192.3 1751.24
  5260.8 1751.57  5346.7 1753.14  5428.1 1755.23  5579.3 1760.55  5624.0 1762.70
  5655.9 1764.10  5663.8 1763.84  5703.0 1764.95  5708.4 1765.62  5726.5 1765.38
  5731.9 1766.19  5740.1 1765.60  5761.8 1766.05  5778.9 1765.20  5831.3 1765.60
#Mann=7,-1,0
  4396.4   0.045       0  4935.4    0.07       0  4993.2    0.07       0
  4998.5    0.07       0  5192.3   0.035       0  5579.3    0.07       0
  5624.0   0.035       0
Bank Sta=4993.2,4998.5
Exp/Cntr=0.3,0.1