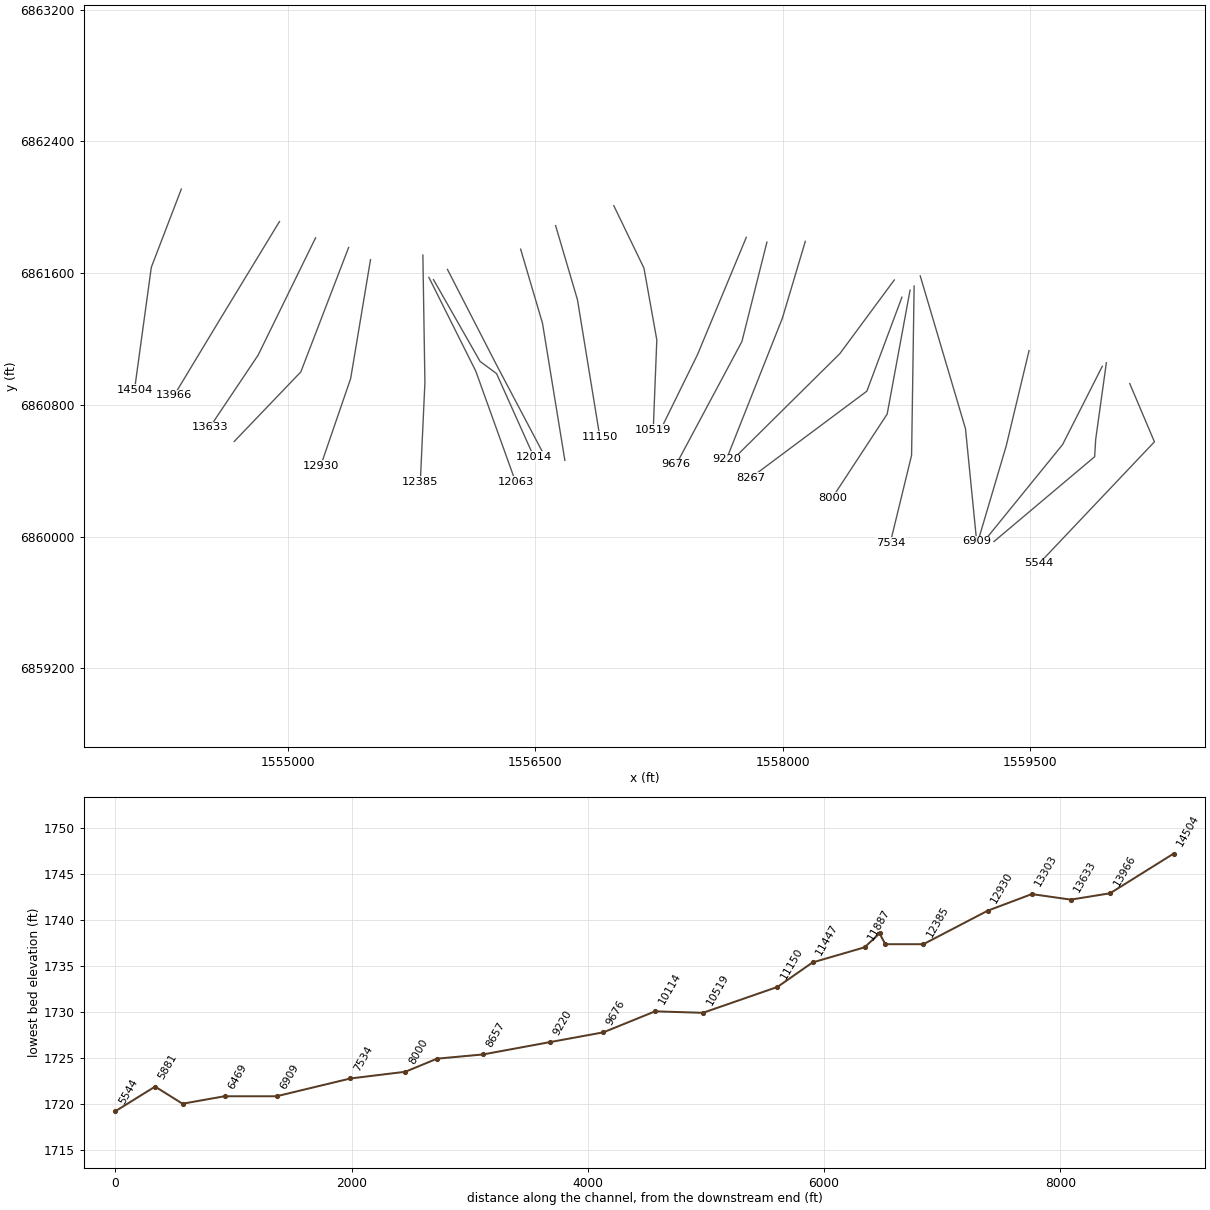
HEC-RAS study Elm 01 47.prj: Elm 01 47 Base Level Engineering

--- Elm 01 47.g01 (geometry) --- (continued)

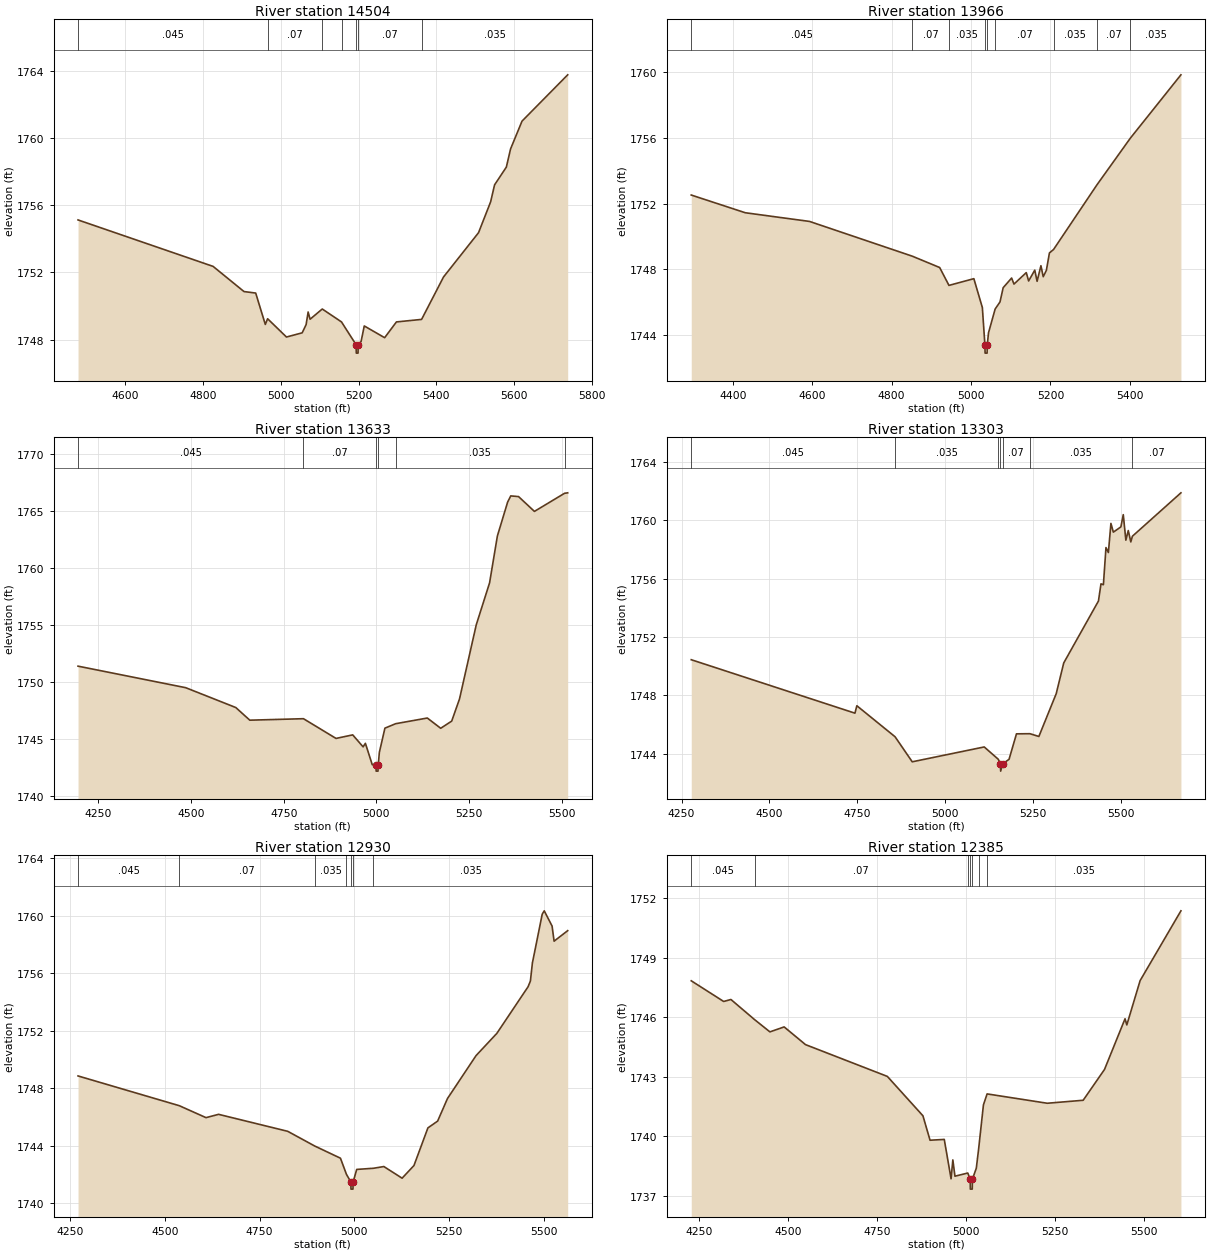
Type RM Length L Ch R = 1,14504,538,538,538
BEGIN DESCRIPTION:
Elm 01 47 14504.01
END DESCRIPTION:
XS GIS Cut Line= 3
      1554353.24      6862110.02      1554171.26      6861635.03
      1554069.48      6860891.73
#Sta/Elev= 30
  4478.7 1755.13  4826.0 1752.36  4905.4 1750.86  4935.5 1750.77  4960.2 1748.90
  4966.1 1749.24  5014.6 1748.15  5055.0 1748.40  5065.1 1748.89  5070.3 1749.64
  5075.3 1749.21  5106.6 1749.82  5156.1 1749.05  5193.6 1747.69  5194.1 1747.19
  5198.6 1747.19  5199.0 1747.69  5206.4 1747.88  5214.6 1748.81  5267.0 1748.11
  5297.3 1749.05  5362.0 1749.20  5418.4 1751.73  5508.4 1754.37  5539.5 1756.21
  5549.6 1757.22  5579.9 1758.28  5590.7 1759.36  5620.2 1761.02  5737.6 1763.78
#Mann=7,-1,0
  4478.7   0.045       0  4966.1    0.07       0  5106.6   0.035       0
  5156.1    0.07       0  5193.6    0.07       0  5199.0    0.07       0
  5362.0   0.035       0
Bank Sta=5193.6,5199
Exp/Cntr=0.3,0.1

Type RM Length L Ch R = 1,13966,333,333,333
BEGIN DESCRIPTION:
Elm 01 47 13966.42
END DESCRIPTION:
XS GIS Cut Line= 3
      1554948.51      6861912.61      1554590.73      6861323.51
      1554310.06      6860857.78
#Sta/Elev= 30
  4295.5 1752.52  4431.5 1751.44  4593.4 1750.91  4852.2 1748.79  4921.0 1748.10
  4944.4 1747.01  5007.1 1747.42  5028.5 1745.66  5034.9 1743.38  5035.4 1742.88
  5040.4 1742.88  5040.9 1743.38  5044.0 1744.12  5060.7 1745.57  5072.9 1746.00
  5080.9 1746.87  5102.2 1747.46  5108.1 1747.09  5139.1 1747.79  5145.0 1747.28
  5160.5 1747.94  5166.3 1747.26  5176.0 1748.21  5181.8 1747.54  5189.7 1747.93
  5197.4 1748.99  5207.8 1749.20  5316.7 1753.13  5401.2 1755.99  5528.5 1759.85
#Mann=9,-1,0
  4295.5   0.045       0  4852.2    0.07       0  4944.4   0.035       0
  5034.9   0.035       0  5040.9   0.035       0  5060.7    0.07       0
  5207.8   0.035       0  5316.7    0.07       0  5401.2   0.035       0
Bank Sta=5034.9,5040.9
Exp/Cntr=0.3,0.1

Type RM Length L Ch R = 1,13633,330,330,330
BEGIN DESCRIPTION:
Elm 01 47 13632.84
END DESCRIPTION:
XS GIS Cut Line= 3
      1555167.52      6861813.96      1554818.97      6861101.44
      1554525.93      6860663.42
#Sta/Elev= 30
  4195.5 1751.40  4485.9 1749.51  4620.9 1747.77  4658.6 1746.66  4803.3 1746.79
  4891.1 1745.06  4936.1 1745.37  4964.1 1744.32  4970.3 1744.63  4988.7 1742.76
  4998.8 1742.69  4999.3 1742.19  5004.3 1742.19  5004.8 1742.69  5007.9 1743.83
  5022.9 1745.96  5051.8 1746.35  5137.2 1746.85  5173.3 1745.95  5203.0 1746.58
  5224.0 1748.52  5269.1 1755.02  5305.1 1758.71  5326.1 1762.82  5353.8 1765.80
  5362.2 1766.34  5383.2 1766.28  5426.0 1764.98  5507.3 1766.57  5515.7 1766.61
#Mann=6,-1,0
  4195.5   0.045       0  4803.3    0.07       0  4998.8    0.07       0
  5004.8    0.07       0  5051.8   0.035       0  5507.3    0.07       0
Bank Sta=4998.8,5004.8
Exp/Cntr=0.3,0.1

Type RM Length L Ch R = 1,13303,373,373,373
BEGIN DESCRIPTION:
Elm 01 47 13302.6
END DESCRIPTION:
XS GIS Cut Line= 3
      1555367.99      6861755.33      1555078.06      6860999.66
      1554674.02      6860577.12
#Sta/Elev= 30
  4277.7 1750.44  4743.7 1746.77  4749.1 1747.28  4857.9 1745.15  4906.8 1743.43
  5111.7 1744.45  5151.5 1743.61  5158.0 1743.29  5158.5 1742.79  5164.1 1743.29
  5182.4 1743.60  5203.5 1745.35  5241.7 1745.36  5267.3 1745.17  5316.7 1748.11
  5338.1 1750.22  5436.9 1754.47  5444.1 1755.65  5451.0 1755.59  5458.3 1758.14
  5465.2 1757.80  5472.4 1759.80  5479.3 1759.20  5500.7 1759.56  5507.6 1760.40
  5514.9 1758.65  5521.8 1759.31  5529.0 1758.53  5533.6 1758.92  5671.7 1761.90
#Mann=7,-1,0
  4277.7   0.045       0  4857.9   0.035       0  5151.5    0.07       0
  5158.0   0.035       0  5164.1    0.07       0  5241.7   0.035       0
  5533.6    0.07       0
Bank Sta=5158,5164.1
Exp/Cntr=0.3,0.1

Type RM Length L Ch R = 1,12930,545,545,545
BEGIN DESCRIPTION:
Elm 01 47 12930.34
END DESCRIPTION:
XS GIS Cut Line= 3
      1555500.60      6861681.25      1555380.32      6860959.56
      1555198.34      6860429.05
#Sta/Elev= 30
  4270.8 1748.86  4538.2 1746.79  4608.6 1745.96  4641.8 1746.19  4824.3 1745.01
  4895.4 1743.99  4963.5 1743.14  4979.3 1742.02  4990.8 1741.49  4991.3 1740.99
  4996.5 1740.99  4997.0 1741.49  5006.4 1742.36  5050.6 1742.44  5078.1 1742.56
  5126.2 1741.75  5157.5 1742.63  5194.4 1745.25  5220.0 1745.72  5246.0 1747.29
  5321.3 1750.27  5376.3 1751.82  5458.7 1755.06  5464.9 1755.46  5470.1 1756.71
  5496.1 1760.11  5501.4 1760.34  5522.1 1759.28  5527.4 1758.23  5563.3 1758.96
#Mann=7,-1,0
  4270.8   0.045       0  4538.2    0.07       0  4895.4   0.035       0
  4979.3    0.07       0  4990.8    0.07       0  4997.0    0.07       0
  5050.6   0.035       0
Bank Sta=4990.8,4997
Exp/Cntr=0.3,0.1

Type RM Length L Ch R = 1,12385,322,322,322
BEGIN DESCRIPTION:
Elm 01 47 12385.07
END DESCRIPTION:
XS GIS Cut Line= 3
      1555818.30      6861709.11      1555830.64      6860934.89
      1555802.88      6860333.44
#Sta/Elev= 30
  4228.7 1747.83  4319.8 1746.79  4340.2 1746.89  4406.5 1745.88  4449.8 1745.26
  4489.8 1745.51  4549.8 1744.62  4779.9 1743.02  4879.9 1741.04  4899.9 1739.81
  4939.9 1739.85  4959.0 1737.87  4964.0 1738.82  4969.9 1738.00  5006.0 1738.16
  5012.7 1737.85  5013.2 1737.35  5018.5 1737.35  5019.0 1737.85  5029.9 1738.40
  5036.4 1739.36  5050.0 1741.59  5060.3 1742.14  5229.4 1741.67  5330.3 1741.82
  5390.3 1743.37  5448.0 1745.92  5453.0 1745.61  5490.4 1747.84  5605.1 1751.35
#Mann=7,-1,0
  4228.7   0.045       0  4406.5    0.07       0  5006.0   0.035       0
  5012.7    0.07       0  5019.0   0.035       0  5036.4    0.07       0
  5060.3   0.035       0
Bank Sta=5012.7,5019
Exp/Cntr=0.3,0.1

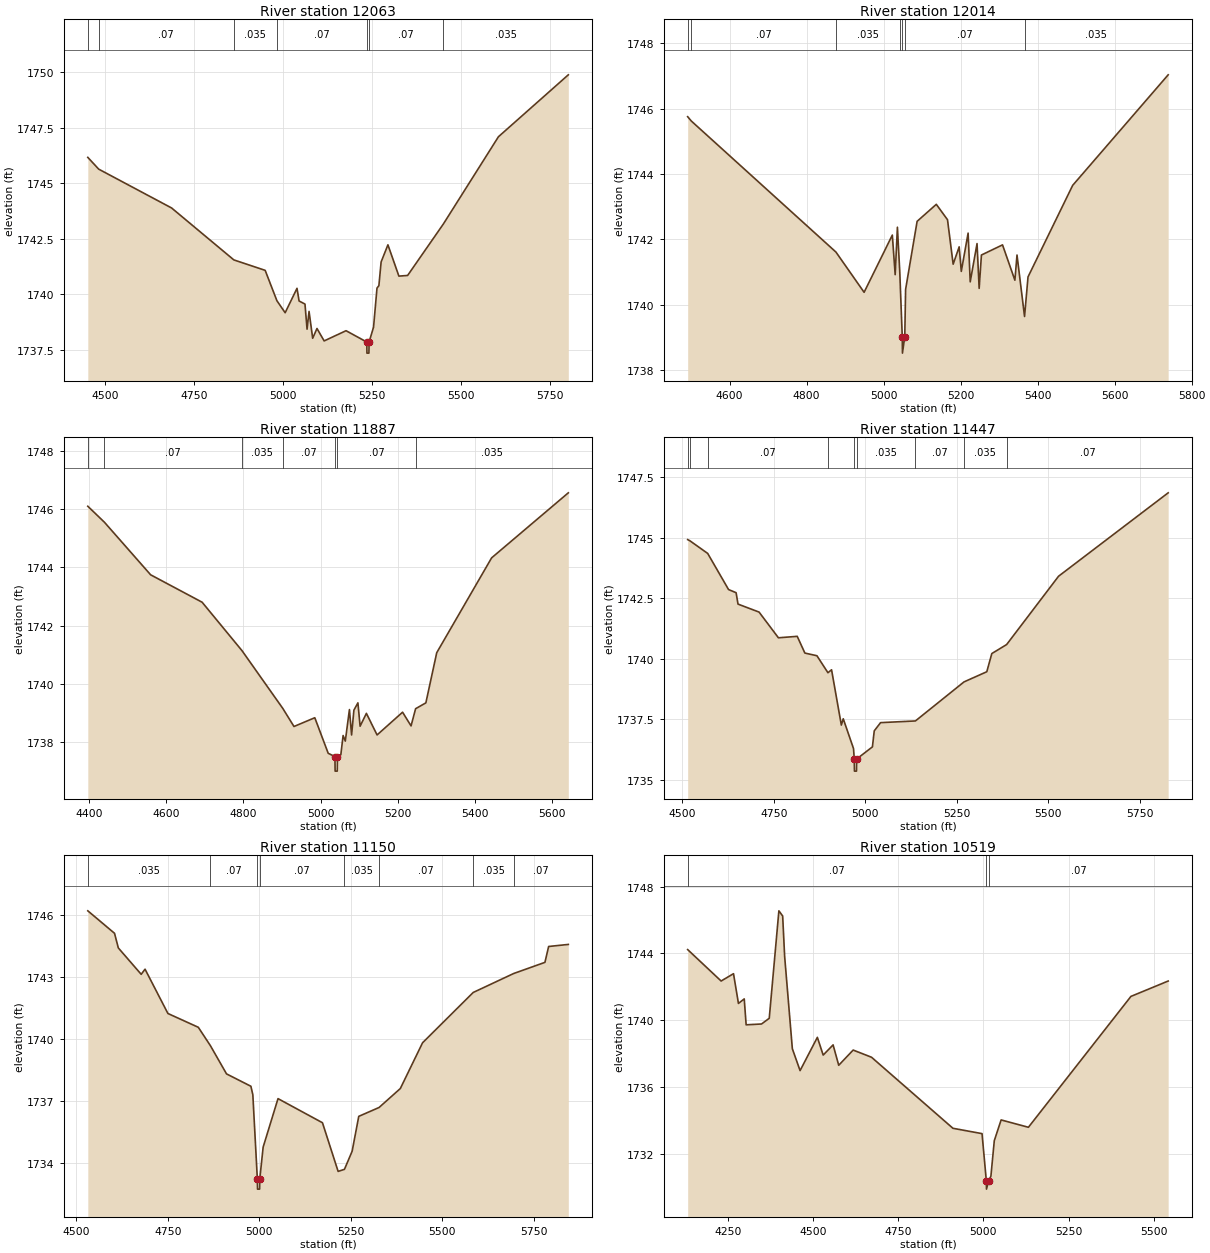
Type RM Length L Ch R = 1,12063,49,49,49
BEGIN DESCRIPTION:
Elm 01 47 12103.55
END DESCRIPTION:
XS GIS Cut Line= 3
      1555854.84      6861573.51      1556139.15      6861004.30
      1556380.05      6860333.29
#Sta/Elev= 30
  4451.5 1746.17  4482.1 1745.64  4686.8 1743.89  4861.6 1741.55  4949.5 1741.08
  4982.5 1739.71  5005.6 1739.17  5038.9 1740.27  5044.7 1739.70  5061.3 1739.56
  5067.1 1738.43  5072.7 1739.23  5082.9 1738.02  5095.0 1738.46  5115.1 1737.90
  5176.6 1738.36  5234.8 1737.85  5235.3 1737.35  5240.8 1737.35  5241.3 1737.85
  5253.8 1738.52  5263.5 1740.28  5268.8 1740.39  5275.1 1741.46  5294.2 1742.23
  5325.0 1740.82  5349.5 1740.85  5449.9 1743.17  5604.5 1747.10  5800.7 1749.89
#Mann=7,-1,0
  4451.5   0.045       0  4482.1    0.07       0  4861.6   0.035       0
  4982.5    0.07       0  5234.8    0.07       0  5241.3    0.07       0
  5449.9   0.035       0
Bank Sta=5234.8,5241.3
Exp/Cntr=0.3,0.1

Type RM Length L Ch R = 1,12014,127,127,127
BEGIN DESCRIPTION:
Elm 01 47 6.0
END DESCRIPTION:
XS GIS Cut Line= 4
      1555882.67      6861559.97      1556165.14      6861063.51
      1556265.13      6860989.46      1556490.71      6860485.35
#Sta/Elev= 30
  4491.1 1745.75  4500.3 1745.62  4876.2 1741.61  4949.3 1740.38  5022.6 1742.13
  5030.0 1740.92  5035.8 1742.37  5041.9 1741.01  5048.4 1739.02  5048.9 1738.52
  5054.9 1739.02  5057.1 1740.47  5087.0 1742.55  5136.8 1743.07  5165.9 1742.60
  5180.6 1741.24  5196.2 1741.77  5201.7 1741.02  5219.4 1742.19  5224.9 1740.70
  5242.6 1741.87  5248.1 1740.50  5254.0 1741.52  5308.8 1741.83  5340.9 1740.75
  5346.4 1741.52  5366.0 1739.64  5375.0 1740.85  5491.0 1743.65  5739.0 1747.03
#Mann=7,-1,0
  4491.1   0.045       0  4500.3    0.07       0  4876.2   0.035       0
  5041.9    0.07       0  5048.4   0.035       0  5054.9    0.07       0
  5366.0   0.035       0
Bank Sta=5048.4,5054.9
Exp/Cntr=0.3,0.1

Type RM Length L Ch R = 1,11887,440,440,440
BEGIN DESCRIPTION:
Elm 01 47 11741.4
END DESCRIPTION:
XS GIS Cut Line= 3
      1555967.58      6861621.73      1556263.04      6861045.72
      1556542.29      6860516.21
#Sta/Elev= 30
  4396.6 1746.09  4439.8 1745.54  4559.5 1743.74  4693.0 1742.80  4796.4 1741.14
  4902.2 1739.16  4931.2 1738.54  4985.2 1738.84  5020.0 1737.62  5037.4 1737.51
  5037.9 1737.01  5043.4 1737.01  5043.9 1737.51  5052.7 1737.57  5058.6 1738.23
  5064.3 1738.04  5075.0 1739.12  5080.6 1738.25  5086.6 1739.10  5097.0 1739.35
  5102.7 1738.55  5119.0 1738.99  5146.7 1738.25  5212.8 1739.03  5234.8 1738.56
  5246.6 1739.15  5273.2 1739.35  5301.4 1741.07  5443.7 1744.32  5642.6 1746.55
#Mann=7,-1,0
  4396.6   0.045       0  4439.8    0.07       0  4796.4   0.035       0
  4902.2    0.07       0  5037.4    0.07       0  5043.9    0.07       0
  5246.6   0.035       0
Bank Sta=5037.4,5043.9
Exp/Cntr=0.3,0.1

Type RM Length L Ch R = 1,11447,297,297,297
BEGIN DESCRIPTION:
Elm 01 47 5.0
END DESCRIPTION:
XS GIS Cut Line= 3
      1556411.22      6861745.11      1556543.85      6861294.79
      1556679.47      6860462.51
#Sta/Elev= 30
  4515.0 1744.92  4520.3 1744.88  4569.7 1744.35  4626.7 1742.86  4647.3 1742.73
  4652.5 1742.26  4710.1 1741.93  4762.9 1740.87  4814.3 1740.93  4835.2 1740.24
  4868.1 1740.13  4898.2 1739.43  4908.1 1739.55  4934.8 1737.27  4940.0 1737.53
  4968.1 1736.30  4970.1 1735.87  4970.6 1735.37  4976.2 1735.37  4976.7 1735.87
  5019.7 1736.37  5024.7 1737.03  5042.0 1737.37  5137.2 1737.44  5269.9 1739.05
  5332.2 1739.47  5345.9 1740.22  5386.3 1740.59  5528.3 1743.41  5827.7 1746.85
#Mann=9,-1,0
  4515.0    0.07       0  4520.3   0.035       0  4569.7    0.07       0
  4898.2   0.035       0  4970.1   0.035       0  4976.7   0.035       0
  5137.2    0.07       0  5269.9   0.035       0  5386.3    0.07       0
Bank Sta=4970.1,4976.7
Exp/Cntr=0.3,0.1

Type RM Length L Ch R = 1,11150,631,631,631
BEGIN DESCRIPTION:
Elm 01 47 11149.76
END DESCRIPTION:
XS GIS Cut Line= 3
      1556623.30      6861887.99      1556755.94      6861437.63
      1556891.64      6860604.90
#Sta/Elev= 30
  4531.0 1746.21  4604.0 1745.12  4614.4 1744.41  4676.9 1743.13  4687.4 1743.38
  4749.9 1741.23  4833.0 1740.56  4866.0 1739.67  4910.1 1738.30  4976.7 1737.70
  4982.0 1737.29  4994.3 1733.21  4994.8 1732.71  5000.5 1732.71  5001.0 1733.21
  5010.2 1734.75  5050.8 1737.10  5172.3 1735.93  5215.1 1733.57  5232.4 1733.67
  5253.4 1734.55  5271.5 1736.24  5327.0 1736.67  5385.1 1737.59  5445.9 1739.81
  5584.3 1742.25  5695.0 1743.17  5780.3 1743.71  5790.4 1744.48  5844.2 1744.58
#Mann=8,-1,0
  4531.0   0.035       0  4866.0    0.07       0  4994.3    0.07       0
  5001.0    0.07       0  5232.4   0.035       0  5327.0    0.07       0
  5584.3   0.035       0  5695.0    0.07       0
Bank Sta=4994.3,5001
Exp/Cntr=0.3,0.1

Type RM Length L Ch R = 1,10519,405,405,405
BEGIN DESCRIPTION:
Elm 01 47 10518.51
END DESCRIPTION:
XS GIS Cut Line= 4
      1556976.21      6862009.11      1557159.22      6861629.73
      1557237.10      6861193.97      1557215.51      6860648.07
#Sta/Elev= 30
  4132.0 1744.23  4230.2 1742.35  4266.5 1742.79  4281.0 1741.01  4298.0 1741.28
  4303.6 1739.73  4348.8 1739.78  4371.4 1740.12  4399.7 1746.55  4410.8 1746.24
  4416.6 1743.82  4439.2 1738.30  4461.9 1736.99  4512.6 1738.98  4529.7 1737.92
  4558.8 1738.53  4575.3 1737.31  4617.7 1738.22  4671.6 1737.79  4910.5 1733.54
  4995.9 1733.22  5008.5 1730.40  5009.0 1729.90  5015.2 1730.40  5021.9 1730.67
  5031.9 1732.80  5051.9 1734.04  5132.0 1733.60  5432.9 1741.43  5542.2 1742.35
#Mann=3,-1,0
  4132.0    0.07       0  5008.5    0.07       0  5015.2    0.07       0
Bank Sta=5008.5,5015.2
Exp/Cntr=0.3,0.1

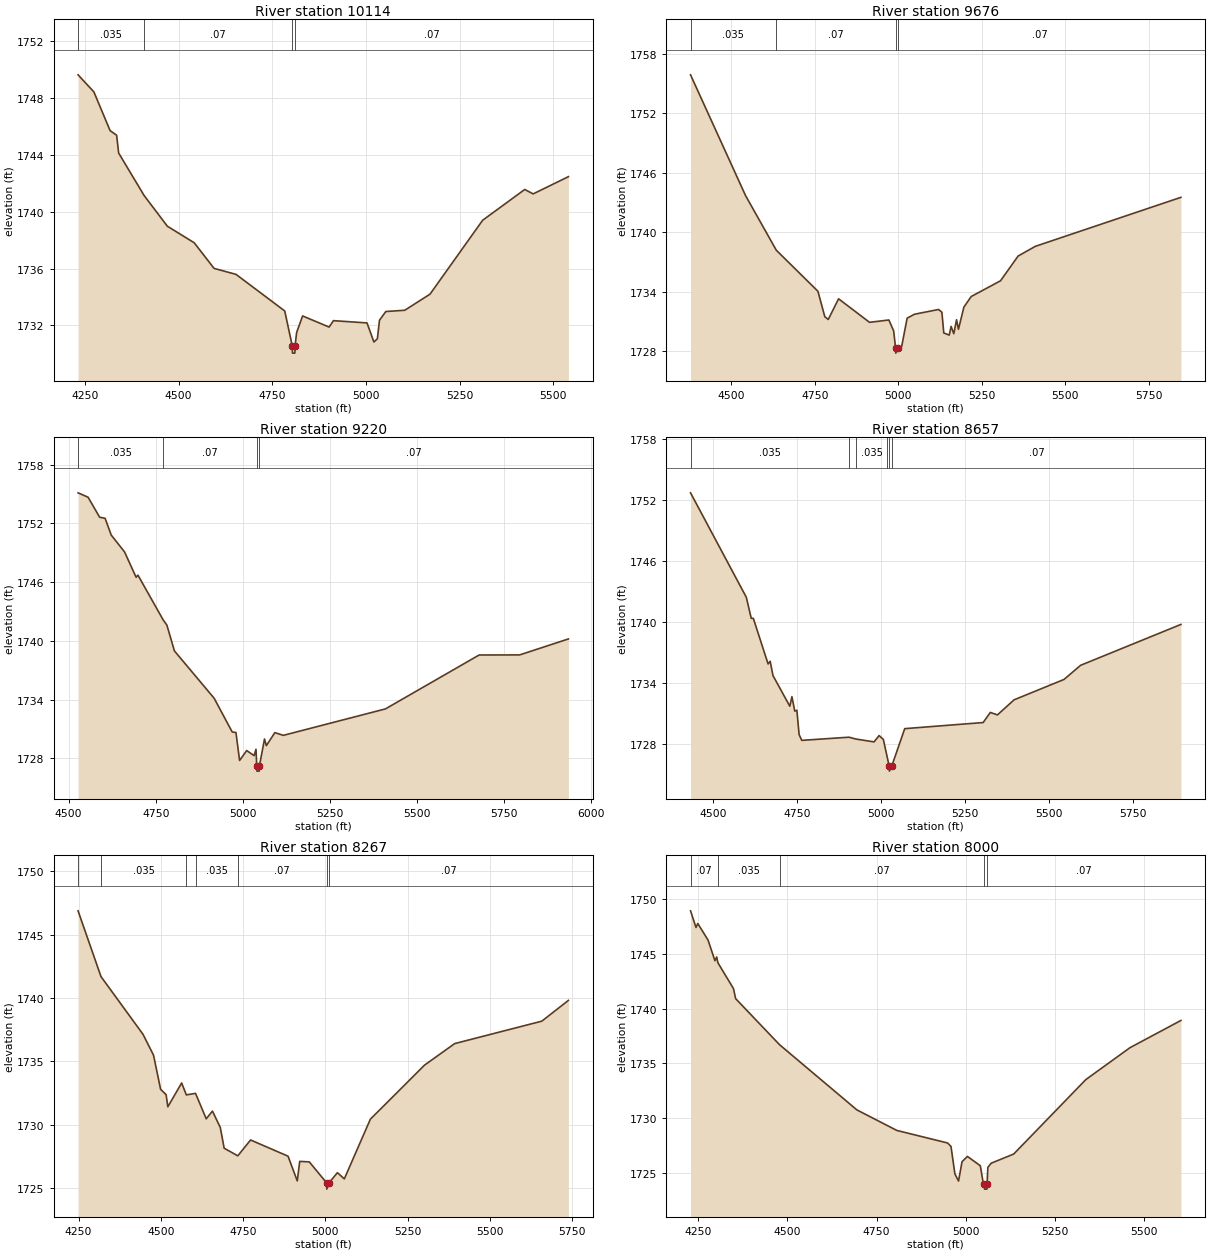
Type RM Length L Ch R = 1,10114,438,438,438
BEGIN DESCRIPTION:
Elm 01 47 10114.48
END DESCRIPTION:
XS GIS Cut Line= 3
      1557779.96      6861817.05      1557483.84      6861104.52
      1557247.03      6860621.68
#Sta/Elev= 30
  4231.3 1749.60  4273.6 1748.40  4316.9 1745.68  4334.3 1745.36  4339.7 1744.11
  4407.6 1741.13  4469.8 1738.97  4541.4 1737.81  4594.5 1736.01  4653.1 1735.59
  4783.2 1733.02  4803.3 1730.56  4803.8 1730.06  4810.2 1730.06  4810.7 1730.56
  4815.0 1731.51  4830.9 1732.67  4901.7 1731.89  4913.3 1732.34  5002.9 1732.18
  5021.3 1730.84  5030.6 1731.07  5036.2 1732.37  5053.1 1732.98  5103.7 1733.07
  5171.1 1734.20  5311.7 1739.39  5424.1 1741.55  5446.6 1741.24  5540.7 1742.45
#Mann=4,-1,0
  4231.3   0.035       0  4407.6    0.07       0  4803.3    0.07       0
  4810.7    0.07       0
Bank Sta=4803.3,4810.7
Exp/Cntr=0.3,0.1

Type RM Length L Ch R = 1,9676,456,456,456
BEGIN DESCRIPTION:
Elm 01 47 9676.177
END DESCRIPTION:
XS GIS Cut Line= 3
      1557904.99      6861787.96      1557753.34      6861184.42
      1557354.98      6860437.96
#Sta/Elev= 30
  4377.7 1755.90  4542.6 1743.69  4634.5 1738.18  4759.2 1734.03  4779.8 1731.46
  4790.1 1731.18  4821.0 1733.27  4913.8 1730.89  4971.6 1731.13  4986.0 1730.02
  4991.8 1728.28  4992.3 1727.78  4999.3 1728.28  5010.0 1728.46  5026.3 1731.31
  5048.3 1731.71  5120.6 1732.19  5130.4 1731.91  5136.1 1729.82  5152.4 1729.60
  5158.0 1730.48  5166.0 1729.74  5174.3 1731.15  5180.0 1730.19  5196.3 1732.43
  5218.2 1733.50  5306.0 1735.09  5358.7 1737.59  5410.2 1738.57  5846.1 1743.52
#Mann=4,-1,0
  4377.7   0.035       0  4634.5    0.07       0  4991.8    0.07       0
  4999.3    0.07       0
Bank Sta=4991.8,4999.3
Exp/Cntr=0.3,0.1

Type RM Length L Ch R = 1,9220,563,563,563
BEGIN DESCRIPTION:
Elm 01 47 9220.49
END DESCRIPTION:
XS GIS Cut Line= 3
      1558137.73      6861792.35      1557998.93      6861326.60
      1557659.84      6860469.63
#Sta/Elev= 30
  4527.0 1755.11  4555.8 1754.66  4589.0 1752.62  4604.6 1752.51  4622.2 1750.80
  4660.5 1749.08  4693.7 1746.49  4698.9 1746.71  4771.2 1742.15  4782.0 1741.61
  4803.6 1738.98  4917.6 1734.15  4969.4 1730.71  4980.2 1730.65  4990.7 1727.80
  5011.1 1728.81  5032.4 1728.29  5037.8 1728.94  5040.0 1727.21  5040.5 1726.71
  5047.0 1726.71  5047.5 1727.21  5062.2 1729.99  5067.5 1729.31  5091.9 1730.64
  5116.2 1730.36  5409.4 1733.06  5678.3 1738.56  5794.7 1738.57  5934.6 1740.20
#Mann=4,-1,0
  4527.0   0.035       0  4771.2    0.07       0  5040.0    0.07       0
  5047.5    0.07       0
Bank Sta=5040,5047.5
Exp/Cntr=0.3,0.1

Type RM Length L Ch R = 1,8657,390,390,390
BEGIN DESCRIPTION:
Elm 01 47 8656.54
END DESCRIPTION:
XS GIS Cut Line= 3
      1558677.48      6861557.91      1558347.46      6861110.69
      1557705.94      6860475.34
#Sta/Elev= 30
  4434.0 1752.70  4599.9 1742.45  4614.6 1740.38  4620.8 1740.38  4664.7 1735.90
  4670.9 1736.17  4679.3 1734.76  4729.4 1731.75  4735.6 1732.69  4744.1 1731.27
  4750.3 1731.36  4757.0 1728.97  4764.9 1728.40  4905.3 1728.71  4926.2 1728.53
  4980.0 1728.25  4995.0 1728.87  5007.6 1728.49  5018.9 1726.78  5025.0 1725.88
  5025.5 1725.38  5032.6 1725.88  5071.2 1729.55  5304.5 1730.15  5325.8 1731.14
  5347.0 1730.90  5396.5 1732.38  5545.0 1734.38  5594.5 1735.77  5892.7 1739.78
#Mann=6,-1,0
  4434.0   0.035       0  4905.3    0.07       0  4926.2   0.035       0
  5018.9    0.07       0  5025.0   0.035       0  5032.6    0.07       0
Bank Sta=5025,5032.6
Exp/Cntr=0.3,0.1

Type RM Length L Ch R = 1,8267,267,267,267
BEGIN DESCRIPTION:
Elm 01 47 8266.55
END DESCRIPTION:
XS GIS Cut Line= 3
      1558723.75      6861453.06      1558510.93      6860882.45
      1557804.63      6860355.04
#Sta/Elev= 30
  4248.4 1746.89  4318.1 1741.70  4445.9 1737.14  4477.9 1735.49  4499.3 1732.80
  4516.0 1732.38  4521.3 1731.42  4563.3 1733.30  4577.5 1732.36  4605.5 1732.48
  4638.0 1730.47  4656.9 1731.08  4680.7 1729.79  4692.5 1728.15  4734.0 1727.55
  4772.8 1728.80  4886.7 1727.52  4914.7 1725.57  4922.2 1727.11  4951.3 1727.07
  5003.8 1725.42  5004.3 1724.92  5011.5 1725.42  5036.8 1726.22  5057.7 1725.73
  5136.9 1730.44  5301.6 1734.71  5393.3 1736.41  5658.0 1738.18  5738.9 1739.82
#Mann=7,-1,0
  4248.4    0.07       0  4318.1   0.035       0  4577.5    0.07       0
  4605.5   0.035       0  4734.0    0.07       0  5003.8    0.07       0
  5011.5    0.07       0
Bank Sta=5003.8,5011.5
Exp/Cntr=0.3,0.1

Type RM Length L Ch R = 1,8000,466,466,466
BEGIN DESCRIPTION:
Elm 01 47 7999.94
END DESCRIPTION:
XS GIS Cut Line= 3
      1558773.10      6861496.22      1558634.30      6860743.66
      1558301.20      6860234.74
#Sta/Elev= 30
  4229.0 1748.96  4244.3 1747.44  4249.3 1747.80  4278.0 1746.29  4297.3 1744.40
  4302.3 1744.74  4305.6 1744.21  4349.2 1741.85  4355.3 1740.93  4478.4 1736.71
  4694.9 1730.75  4806.8 1728.87  4949.2 1727.72  4958.6 1727.40  4969.5 1724.89
  4979.7 1724.24  4989.5 1726.01  5004.6 1726.49  5040.7 1725.64  5048.8 1724.06
  5052.0 1724.00  5052.5 1723.50  5059.2 1723.50  5059.7 1724.00  5061.8 1725.49
  5071.0 1725.87  5134.2 1726.71  5336.2 1733.52  5459.9 1736.44  5602.5 1738.93
#Mann=5,-1,0
  4229.0    0.07       0  4305.6   0.035       0  4478.4    0.07       0
  5052.0    0.07       0  5059.7    0.07       0
Bank Sta=5052,5059.7
Exp/Cntr=0.3,0.1

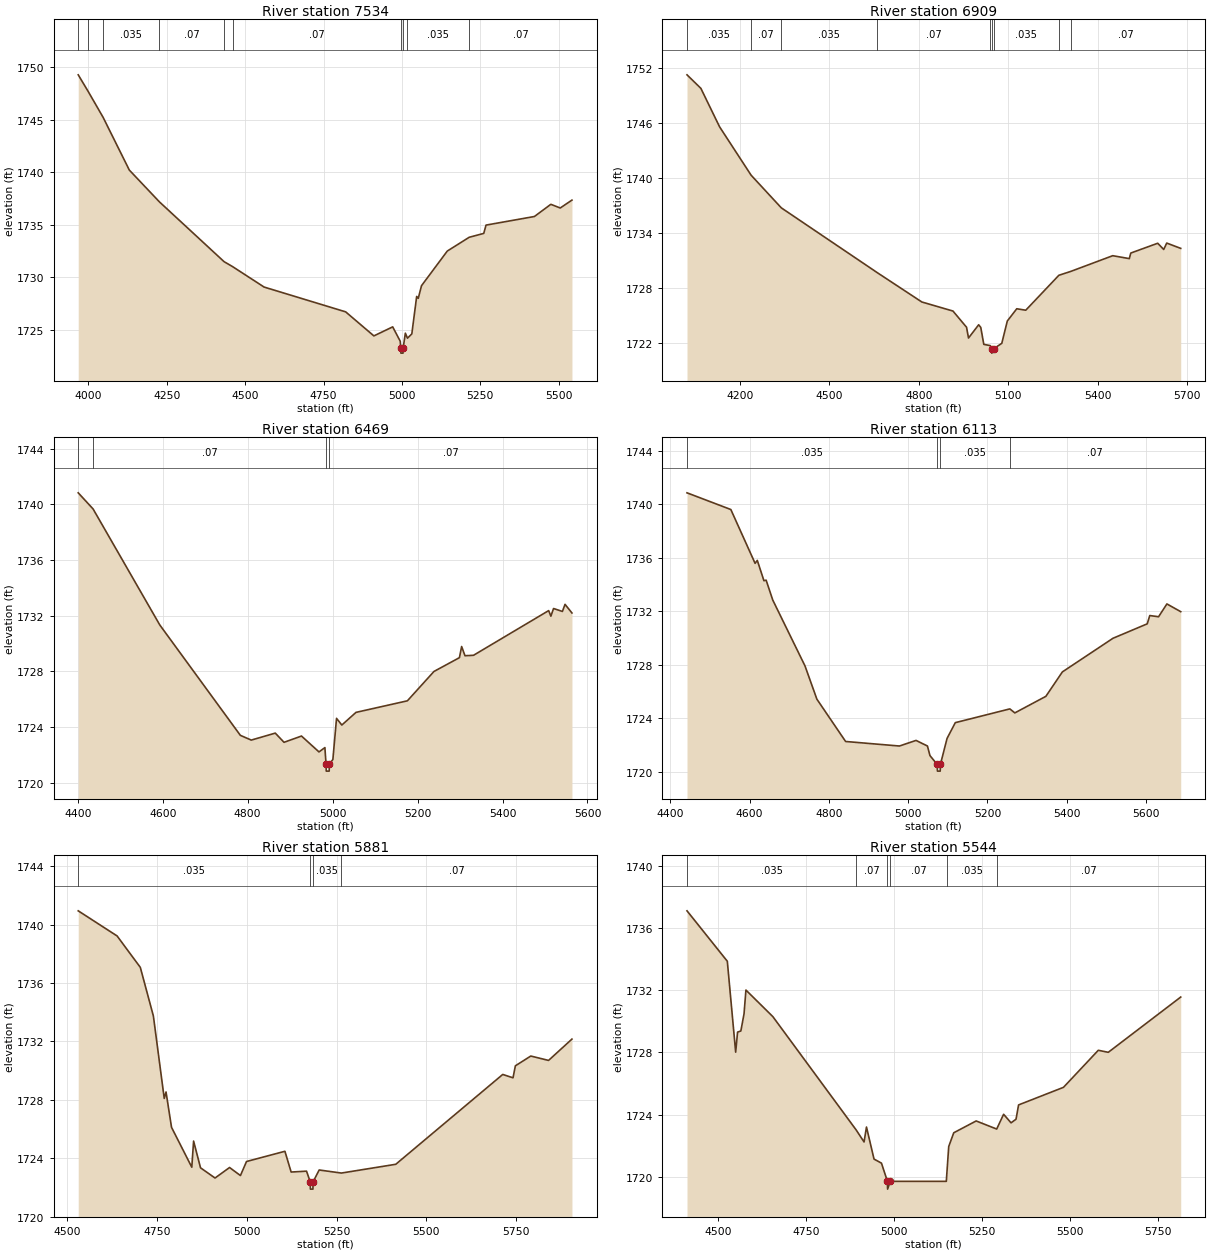
Type RM Length L Ch R = 1,7534,625,625,625
BEGIN DESCRIPTION:
Elm 01 47 7533.69
END DESCRIPTION:
XS GIS Cut Line= 3
      1558797.78      6861520.96      1558782.35      6860493.82
      1558653.15      6859961.63
#Sta/Elev= 30
  3967.4 1749.27  3999.5 1747.67  4046.8 1745.22  4130.4 1740.20  4226.5 1737.17
  4432.6 1731.48  4460.2 1731.00  4560.4 1729.06  4820.5 1726.70  4910.5 1724.41
  4970.5 1725.27  4994.6 1723.90  4996.2 1723.27  4996.7 1722.77  5003.5 1722.77
  5004.0 1723.27  5010.9 1724.67  5017.6 1724.19  5031.5 1724.60  5047.0 1728.17
  5052.1 1727.99  5062.4 1729.19  5144.7 1732.49  5214.5 1733.80  5261.0 1734.17
  5268.2 1734.96  5422.6 1735.78  5475.0 1736.94  5504.9 1736.59  5542.3 1737.34
#Mann=10,-1,0
  3967.4   0.035       0  3999.5    0.07       0  4046.8   0.035       0
  4226.5    0.07       0  4432.6   0.035       0  4460.2    0.07       0
  4996.2    0.07       0  5004.0    0.07       0  5017.6   0.035       0
  5214.5    0.07       0
Bank Sta=4996.2,5004
Exp/Cntr=0.3,0.1

Type RM Length L Ch R = 1,6909,440,440,440
BEGIN DESCRIPTION:
Elm 01 47 6908.68
END DESCRIPTION:
XS GIS Cut Line= 3
      1558834.79      6861582.60      1559109.29      6860654.21
      1559176.97      6859971.28
#Sta/Elev= 30
  4023.4 1751.26  4069.9 1749.78  4132.5 1745.58  4238.2 1740.29  4339.4 1736.72
  4661.7 1729.62  4810.3 1726.43  4914.6 1725.44  4960.1 1723.67  4966.7 1722.49
  5000.7 1723.94  5007.8 1723.65  5017.9 1721.80  5039.7 1721.66  5044.1 1721.34
  5044.6 1720.84  5051.9 1721.34  5078.2 1721.91  5096.7 1724.35  5128.4 1725.69
  5158.5 1725.53  5269.5 1729.35  5309.2 1729.77  5450.0 1731.49  5505.5 1731.17
  5510.5 1731.78  5600.7 1732.85  5620.8 1732.17  5630.9 1732.87  5677.8 1732.29
#Mann=9,-1,0
  4023.4   0.035       0  4238.2    0.07       0  4339.4   0.035       0
  4661.7    0.07       0  5039.7   0.035       0  5044.1    0.07       0
  5051.9   0.035       0  5269.5   0.035       0  5309.2    0.07       0
Bank Sta=5044.1,5051.9
Exp/Cntr=0.3,0.1

Type RM Length L Ch R = 1,6469,356,356,356
BEGIN DESCRIPTION:
Elm 01 47 6468.86
END DESCRIPTION:
XS GIS Cut Line= 3
      1559494.84      6861129.20      1559356.04      6860549.34
      1559195.65      6860006.48
#Sta/Elev= 30
  4401.1 1740.83  4436.1 1739.67  4593.1 1731.34  4782.8 1723.41  4808.5 1723.07
  4865.0 1723.57  4885.6 1722.91  4926.7 1723.36  4967.9 1722.22  4981.8 1722.53
  4984.5 1721.34  4985.0 1720.84  4991.9 1720.84  4992.4 1721.34  5000.6 1721.68
  5009.2 1724.63  5021.7 1724.15  5055.0 1725.06  5176.0 1725.89  5238.6 1728.00
  5298.5 1728.99  5303.7 1729.79  5311.6 1729.13  5331.7 1729.16  5508.6 1732.37
  5513.8 1731.97  5520.1 1732.52  5541.0 1732.31  5547.1 1732.82  5563.4 1732.20
#Mann=4,-1,0
  4401.1   0.035       0  4436.1    0.07       0  4984.5    0.07       0
  4992.4    0.07       0
Bank Sta=4984.5,4992.4
Exp/Cntr=0.3,0.1

Type RM Length L Ch R = 1,6113,232,232,232
BEGIN DESCRIPTION:
Elm 01 47 6112.76
END DESCRIPTION:
XS GIS Cut Line= 3
      1559938.99      6861033.59      1559698.40      6860558.60
      1559249.03      6860004.58
#Sta/Elev= 30
  4442.0 1740.87  4552.6 1739.62  4613.8 1735.59  4619.4 1735.81  4636.1 1734.29
  4641.7 1734.33  4658.4 1732.84  4739.7 1727.91  4769.7 1725.42  4842.2 1722.25
  4978.0 1721.91  5019.9 1722.33  5048.7 1721.91  5055.1 1721.19  5073.4 1720.53
  5073.9 1720.03  5080.9 1720.03  5081.4 1720.53  5098.2 1722.48  5119.0 1723.66
  5256.6 1724.69  5269.2 1724.39  5347.5 1725.63  5389.2 1727.46  5517.0 1729.98
  5603.3 1731.06  5609.7 1731.68  5631.9 1731.59  5652.9 1732.55  5687.8 1731.97
#Mann=4,-1,0
  4442.0   0.035       0  5073.4   0.035       0  5081.4   0.035       0
  5256.6    0.07       0
Bank Sta=5073.4,5081.4
Exp/Cntr=0.3,0.1

Type RM Length L Ch R = 1,5881,337,337,337
BEGIN DESCRIPTION:
Elm 01 47 5880.53
END DESCRIPTION:
XS GIS Cut Line= 4
      1559963.66      6861055.19      1559898.89      6860589.44
      1559892.72      6860484.57      1559282.02      6859969.49
#Sta/Elev= 30
  4530.9 1740.94  4639.1 1739.22  4703.7 1737.07  4740.1 1733.74  4770.3 1728.10
  4775.3 1728.54  4790.6 1726.12  4847.0 1723.39  4852.0 1725.18  4871.3 1723.35
  4911.7 1722.65  4952.1 1723.37  4982.4 1722.82  4999.3 1723.78  5106.2 1724.48
  5123.5 1723.06  5166.4 1723.12  5176.6 1722.39  5177.1 1721.89  5184.2 1721.89
  5184.7 1722.39  5201.5 1723.20  5263.4 1722.99  5414.7 1723.59  5712.5 1729.74
  5741.1 1729.51  5747.6 1730.33  5790.5 1731.00  5840.0 1730.70  5905.1 1732.16
#Mann=4,-1,0
  4530.9   0.035       0  5176.6   0.035       0  5184.7   0.035       0
  5263.4    0.07       0
Bank Sta=5176.6,5184.7
Exp/Cntr=0.3,0.1

Type RM Length L Ch R = 1,5544,312,312,312
BEGIN DESCRIPTION:
Elm 01 47 5615.2
END DESCRIPTION:
XS GIS Cut Line= 3
      1560105.55      6860928.68      1560255.16      6860575.07
      1559556.12      6859836.33
#Sta/Elev= 30
  4412.6 1737.09  4527.0 1733.85  4550.7 1728.01  4556.1 1729.30  4565.4 1729.37
  4574.4 1730.47  4579.8 1732.00  4656.3 1730.29  4892.7 1723.01  4915.0 1722.24
  4921.9 1723.20  4943.3 1721.14  4964.4 1720.88  4981.3 1719.71  4981.8 1719.21
  4989.4 1719.71  5148.4 1719.71  5151.5 1720.72  5155.3 1721.95  5169.5 1722.83
  5233.1 1723.59  5291.4 1723.07  5311.0 1724.02  5332.1 1723.47  5346.2 1723.70
  5353.5 1724.62  5480.9 1725.75  5579.7 1728.13  5608.0 1728.00  5813.6 1731.55
#Mann=6,-1,0
  4412.6   0.035       0  4892.7    0.07       0  4981.3    0.07       0
  4989.4    0.07       0  5151.5   0.035       0  5291.4    0.07       0
Bank Sta=4981.3,4989.4
Exp/Cntr=0.3,0.1