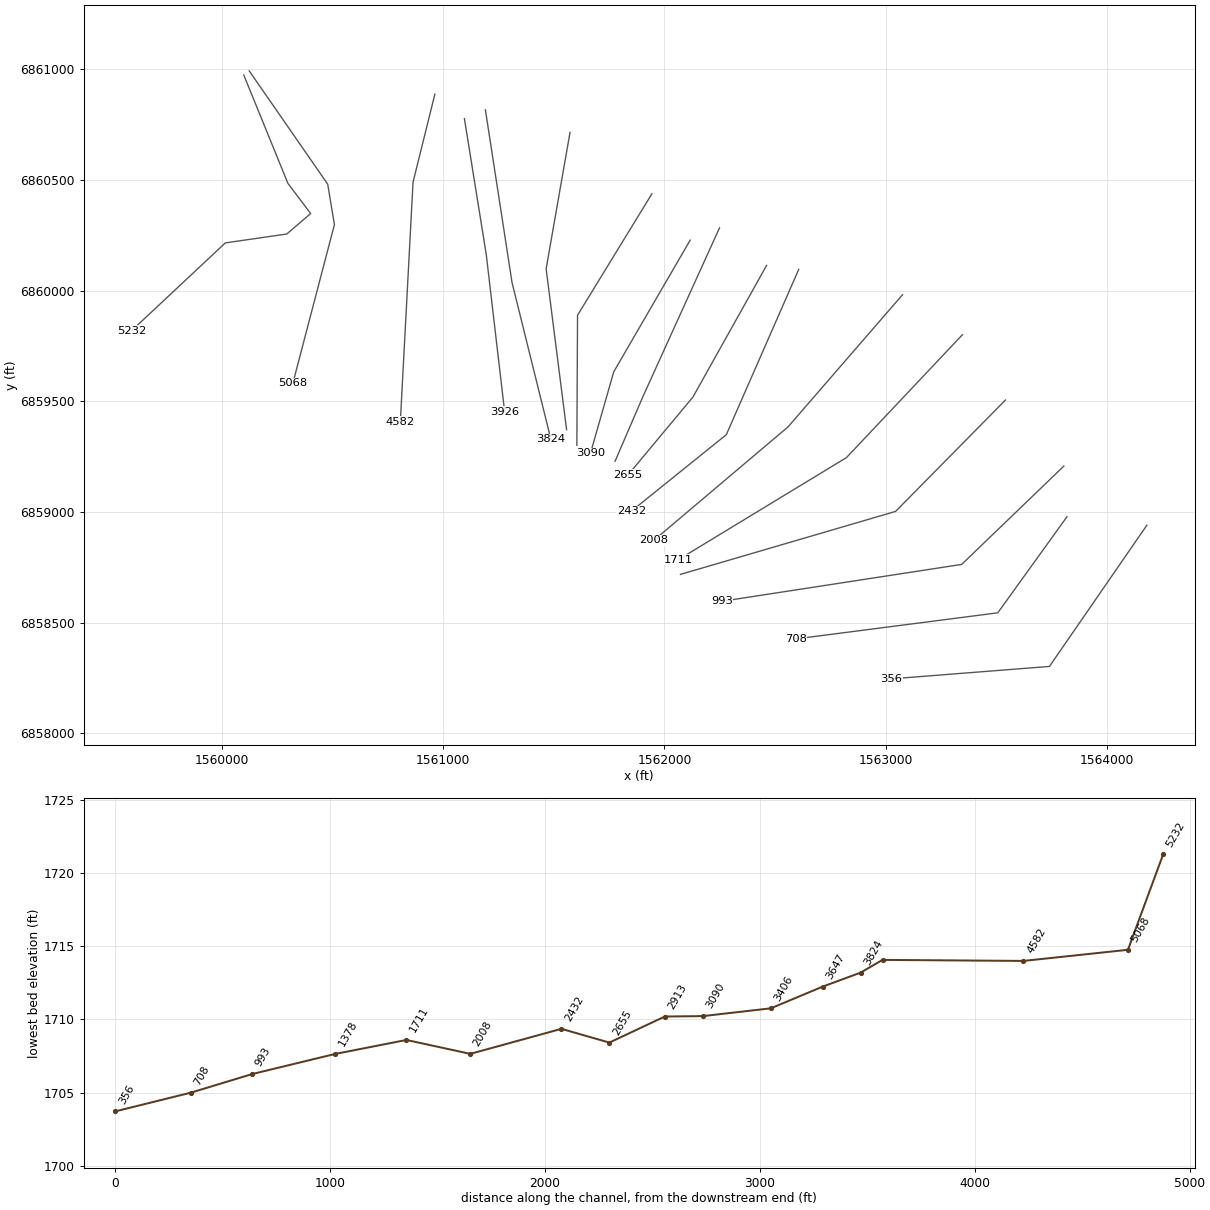
HEC-RAS study Elm 01 47.prj: Elm 01 47 Base Level Engineering

--- Elm 01 47.g01 (geometry) --- (continued)

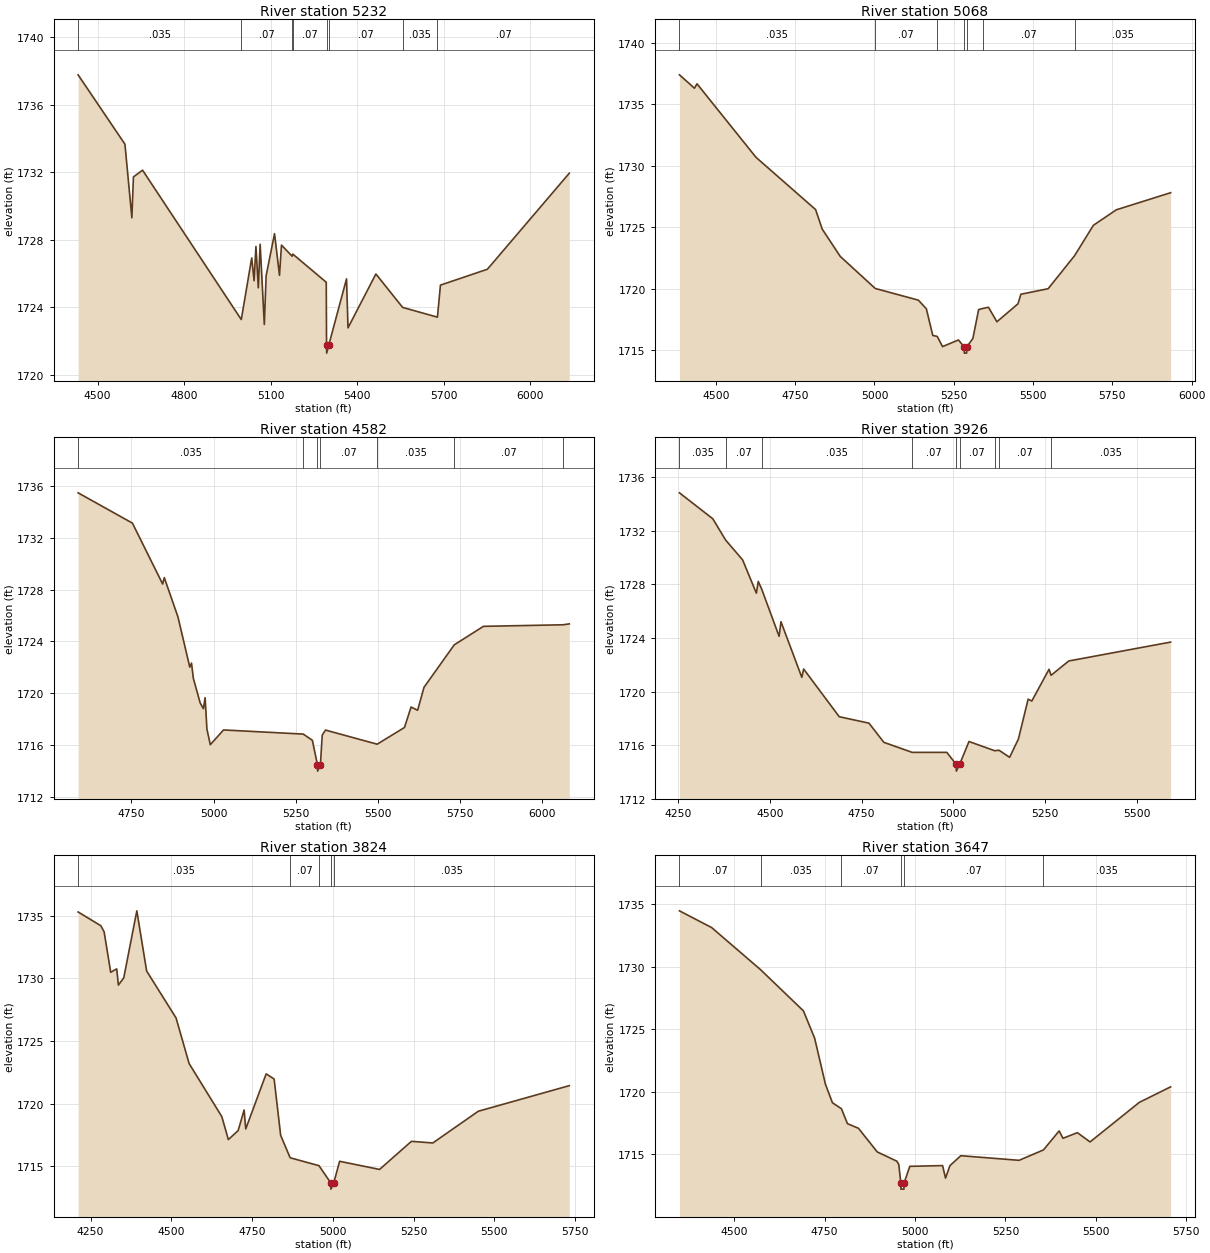
Type RM Length L Ch R = 1,5232,164,164,164
BEGIN DESCRIPTION:
Elm 01 47 5201.24
END DESCRIPTION:
XS GIS Cut Line= 6
      1560099.38      6860974.95      1560298.88      6860485.21
      1560401.63      6860348.86      1560293.68      6860256.33
      1560016.09      6860216.23      1559592.34      6859819.33
#Sta/Elev= 30
  4432.4 1737.77  4594.8 1733.66  4618.8 1729.30  4624.2 1731.72  4655.9 1732.12
  4998.1 1723.27  5034.3 1726.92  5042.6 1725.57  5048.9 1727.60  5057.2 1725.15
  5063.5 1727.73  5078.0 1722.98  5084.3 1725.87  5113.4 1728.36  5130.6 1725.89
  5137.5 1727.68  5174.6 1727.02  5176.6 1727.15  5292.7 1725.48  5293.7 1721.78
  5294.2 1721.28  5301.8 1721.78  5363.0 1725.68  5368.1 1722.78  5464.8 1725.97
  5557.4 1723.99  5678.1 1723.41  5688.6 1725.31  5851.3 1726.25  6135.2 1731.94
#Mann=8,-1,0
  4432.4   0.035       0  4998.1    0.07       0  5174.6   0.035       0
  5176.6    0.07       0  5293.7    0.07       0  5301.8    0.07       0
  5557.4   0.035       0  5678.1    0.07       0
Bank Sta=5293.7,5301.8
Exp/Cntr=0.3,0.1

Type RM Length L Ch R = 1,5068,486,486,486
BEGIN DESCRIPTION:
Elm 01 47 5067.71
END DESCRIPTION:
XS GIS Cut Line= 4
      1560124.04      6860993.50      1560478.74      6860481.49
      1560508.98      6860298.56      1560321.28      6859582.43
#Sta/Elev= 30
  4385.1 1737.39  4432.5 1736.30  4440.4 1736.66  4626.4 1730.68  4814.3 1726.43
  4835.2 1724.84  4892.0 1722.62  5002.4 1720.01  5138.3 1719.06  5163.5 1718.36
  5183.8 1716.19  5197.8 1716.11  5214.6 1715.28  5264.7 1715.82  5282.9 1715.25
  5283.4 1714.75  5290.5 1714.75  5291.0 1715.25  5310.3 1715.95  5328.4 1718.29
  5342.5 1718.39  5359.4 1718.48  5385.9 1717.30  5452.4 1718.76  5461.5 1719.54
  5547.5 1719.99  5630.7 1722.67  5690.2 1725.15  5762.5 1726.41  5933.7 1727.80
#Mann=7,-1,0
  4385.1   0.035       0  5002.4    0.07       0  5197.8   0.035       0
  5282.9   0.035       0  5291.0   0.035       0  5342.5    0.07       0
  5630.7   0.035       0
Bank Sta=5282.9,5291
Exp/Cntr=0.3,0.1

Type RM Length L Ch R = 1,4582,656,656,656
BEGIN DESCRIPTION:
Elm 01 47 4582.4
END DESCRIPTION:
XS GIS Cut Line= 3
      1560962.97      6860888.57      1560864.29      6860490.74
      1560806.81      6859407.05
#Sta/Elev= 30
  4587.7 1735.48  4753.1 1733.14  4845.0 1728.44  4850.1 1728.93  4891.5 1725.91
  4927.7 1722.02  4932.9 1722.33  4938.6 1721.15  4959.2 1719.26  4969.1 1718.81
  4974.3 1719.66  4979.8 1717.24  4990.1 1716.03  5030.4 1717.17  5273.1 1716.85
  5300.8 1716.37  5316.2 1714.49  5316.7 1713.99  5325.3 1714.49  5330.8 1716.77
  5340.8 1717.16  5498.0 1716.07  5581.2 1717.36  5601.2 1718.94  5621.2 1718.69
  5640.6 1720.46  5732.6 1723.74  5821.5 1725.17  6063.6 1725.29  6082.8 1725.36
#Mann=7,-1,0
  4587.7   0.035       0  5273.1    0.07       0  5316.2   0.035       0
  5325.3    0.07       0  5498.0   0.035       0  5732.6    0.07       0
  6063.6   0.035       0
Bank Sta=5316.2,5325.3
Exp/Cntr=0.3,0.1

Type RM Length L Ch R = 1,3926,102,102,102
BEGIN DESCRIPTION:
Elm 01 47 4128.97
END DESCRIPTION:
XS GIS Cut Line= 3
      1561096.38      6860777.87      1561195.08      6860164.08
      1561278.28      6859452.30
#Sta/Elev= 30
  4253.9 1734.83  4344.9 1732.89  4379.6 1731.31  4425.9 1729.83  4463.5 1727.34
  4468.6 1728.22  4478.3 1727.62  4525.4 1724.12  4530.5 1725.21  4587.3 1721.06
  4592.3 1721.68  4689.3 1718.12  4770.3 1717.64  4810.8 1716.21  4887.8 1715.46
  4982.4 1715.46  5007.9 1714.56  5008.4 1714.06  5017.2 1714.56  5042.8 1716.27
  5113.1 1715.58  5124.5 1715.62  5153.5 1715.09  5177.5 1716.46  5203.9 1719.43
  5213.9 1719.29  5260.9 1721.66  5266.4 1721.21  5314.6 1722.28  5592.2 1723.69
#Mann=9,-1,0
  4253.9   0.035       0  4379.6    0.07       0  4478.3   0.035       0
  4887.8    0.07       0  5007.9    0.07       0  5017.2    0.07       0
  5113.1   0.035       0  5124.5    0.07       0  5266.4   0.035       0
Bank Sta=5007.9,5017.2
Exp/Cntr=0.3,0.1

Type RM Length L Ch R = 1,3824,177,177,177
BEGIN DESCRIPTION:
Elm 01 47 3824.33
END DESCRIPTION:
XS GIS Cut Line= 3
      1561191.23      6860817.69      1561311.52      6860037.34
      1561487.32      6859327.96
#Sta/Elev= 30
  4211.4 1735.29  4281.9 1734.19  4292.0 1733.70  4312.3 1730.48  4331.0 1730.75
  4336.1 1729.46  4352.7 1730.03  4393.2 1735.38  4423.6 1730.58  4514.6 1726.84
  4555.1 1723.20  4656.3 1718.97  4676.5 1717.14  4706.9 1717.86  4725.3 1719.50
  4730.3 1717.99  4793.5 1722.38  4818.2 1721.97  4838.4 1717.48  4867.8 1715.69
  4957.0 1715.06  4993.5 1713.69  4994.0 1713.19  5002.8 1713.69  5020.9 1715.41
  5144.5 1714.76  5243.2 1717.00  5309.4 1716.87  5450.2 1719.40  5731.8 1721.44
#Mann=5,-1,0
  4211.4   0.035       0  4867.8    0.07       0  4957.0   0.035       0
  4993.5   0.035       0  5002.8   0.035       0
Bank Sta=4993.5,5002.8
Exp/Cntr=0.3,0.1

Type RM Length L Ch R = 1,3647,241,241,241
BEGIN DESCRIPTION:
Elm 01 47 3647
END DESCRIPTION:
XS GIS Cut Line= 3
      1561573.68      6860715.85      1561465.73      6860099.03
      1561558.14      6859372.07
#Sta/Elev= 30
  4348.2 1734.46  4437.4 1733.12  4572.6 1729.76  4691.2 1726.47  4722.2 1724.29
  4752.1 1720.61  4771.5 1719.13  4796.4 1718.65  4813.0 1717.46  4843.5 1717.09
  4895.5 1715.20  4949.8 1714.46  4955.1 1714.19  4960.6 1712.73  4961.1 1712.23
  4969.4 1712.23  4969.9 1712.73  4985.5 1714.05  5076.2 1714.11  5084.4 1713.11
  5096.4 1714.10  5126.6 1714.90  5287.9 1714.53  5355.3 1715.36  5398.8 1716.88
  5409.3 1716.29  5449.2 1716.74  5484.3 1716.00  5620.6 1719.16  5707.2 1720.40
#Mann=6,-1,0
  4348.2    0.07       0  4572.6   0.035       0  4796.4    0.07       0
  4960.6    0.07       0  4969.9    0.07       0  5355.3   0.035       0
Bank Sta=4960.6,4969.9
Exp/Cntr=0.3,0.1

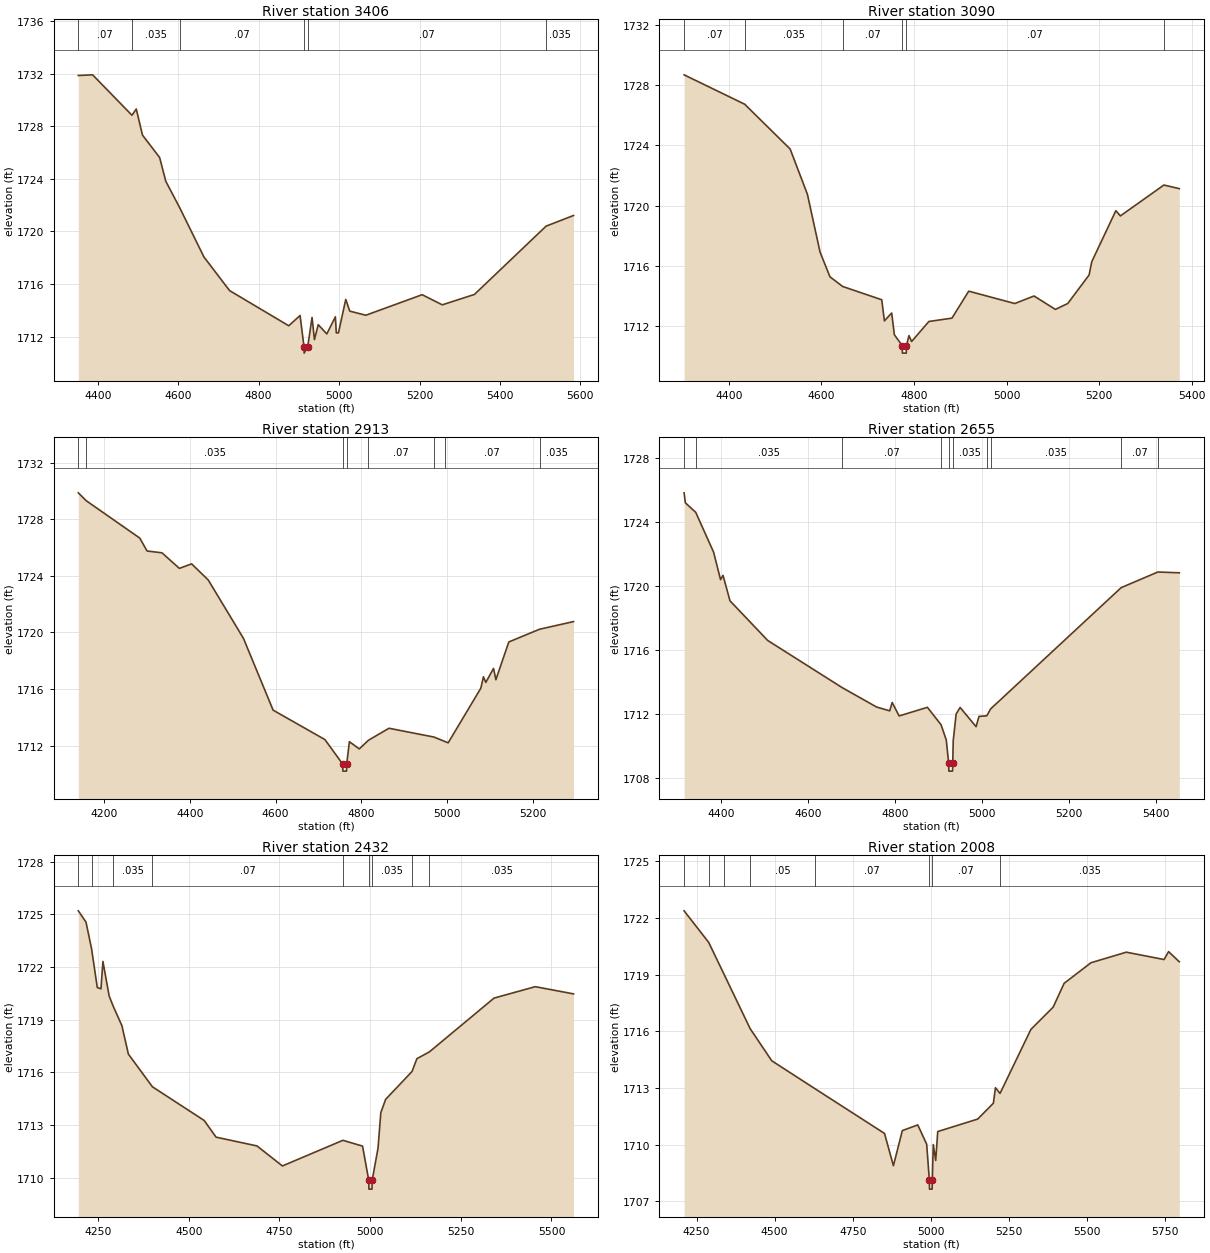
Type RM Length L Ch R = 1,3406,316,316,316
BEGIN DESCRIPTION:
Elm 01 47 3406
END DESCRIPTION:
XS GIS Cut Line= 3
      1561943.82      6860438.33      1561607.61      6859889.29
      1561604.54      6859301.60
#Sta/Elev= 30
  4351.5 1731.85  4387.1 1731.90  4484.9 1728.83  4495.7 1729.30  4511.1 1727.32
  4553.7 1725.62  4569.1 1723.81  4603.2 1721.83  4663.9 1718.06  4727.8 1715.50
  4874.8 1712.83  4903.0 1713.61  4912.7 1711.25  4913.2 1710.75  4922.0 1711.25
  4932.8 1713.46  4938.7 1711.78  4948.2 1712.91  4969.5 1712.21  4990.8 1713.51
  4993.1 1712.29  4998.4 1712.29  5016.6 1714.83  5026.6 1713.94  5066.6 1713.63
  5206.6 1715.19  5256.6 1714.42  5336.6 1715.21  5514.8 1720.40  5583.0 1721.21
#Mann=6,-1,0
  4351.5    0.07       0  4484.9   0.035       0  4603.2    0.07       0
  4912.7    0.07       0  4922.0    0.07       0  5514.8   0.035       0
Bank Sta=4912.7,4922
Exp/Cntr=0.3,0.1

Type RM Length L Ch R = 1,3090,177,177,177
BEGIN DESCRIPTION:
Elm 01 47 3090.25
END DESCRIPTION:
XS GIS Cut Line= 3
      1562116.52      6860228.56      1561771.08      6859633.29
      1561666.20      6859266.22
#Sta/Elev= 30
  4303.4 1728.68  4434.3 1726.73  4532.5 1723.76  4569.8 1720.76  4597.1 1716.93
  4618.6 1715.28  4646.1 1714.64  4730.4 1713.76  4736.2 1712.36  4751.9 1712.88
  4757.7 1711.44  4774.6 1710.72  4775.1 1710.22  4783.4 1710.22  4783.9 1710.72
  4789.2 1711.38  4795.0 1710.99  4832.3 1712.32  4882.1 1712.54  4918.4 1714.33
  5017.9 1713.51  5059.5 1714.01  5105.6 1713.12  5132.3 1713.51  5178.4 1715.40
  5184.3 1716.29  5236.3 1719.67  5246.0 1719.32  5340.1 1721.37  5373.4 1721.13
#Mann=6,-1,0
  4303.4    0.07       0  4434.3   0.035       0  4646.1    0.07       0
  4774.6    0.07       0  4783.9    0.07       0  5340.1   0.035       0
Bank Sta=4774.6,4783.9
Exp/Cntr=0.3,0.1

Type RM Length L Ch R = 1,2913,258,258,258
BEGIN DESCRIPTION:
Elm 01 47 2913.49
END DESCRIPTION:
XS GIS Cut Line= 3
      1562249.15      6860284.08      1561900.63      6859516.09
      1561777.26      6859229.26
#Sta/Elev= 30
  4139.7 1729.86  4158.3 1729.30  4283.2 1726.66  4300.1 1725.75  4334.9 1725.62
  4375.6 1724.52  4404.1 1724.84  4442.9 1723.70  4525.0 1719.58  4594.3 1714.50
  4715.2 1712.42  4756.6 1710.69  4757.1 1710.19  4765.5 1710.19  4766.0 1710.69
  4772.3 1712.27  4795.4 1711.76  4816.7 1712.37  4864.6 1713.22  4969.4 1712.60
  4994.8 1712.29  5002.8 1712.19  5079.0 1716.05  5085.1 1716.86  5090.6 1716.46
  5108.7 1717.45  5114.1 1716.65  5144.3 1719.32  5216.3 1720.22  5295.3 1720.76
#Mann=8,-1,0
  4139.7    0.07       0  4158.3   0.035       0  4756.6    0.07       0
  4766.0   0.035       0  4816.7    0.07       0  4969.4   0.035       0
  4994.8    0.07       0  5216.3   0.035       0
Bank Sta=4756.6,4766
Exp/Cntr=0.3,0.1

Type RM Length L Ch R = 1,2655,223,223,223
BEGIN DESCRIPTION:
Elm 01 47 2655.1
END DESCRIPTION:
XS GIS Cut Line= 3
      1562461.95      6860114.41      1562128.87      6859519.17
      1561835.85      6859167.55
#Sta/Elev= 30
  4314.6 1725.81  4317.4 1725.19  4341.4 1724.59  4382.5 1722.10  4398.5 1720.38
  4404.2 1720.65  4420.2 1719.06  4507.0 1716.58  4677.9 1713.64  4757.4 1712.42
  4787.8 1712.18  4793.5 1712.70  4809.5 1711.86  4874.6 1712.40  4906.0 1711.31
  4918.0 1710.36  4923.5 1708.91  4924.0 1708.41  4932.4 1708.41  4932.9 1708.91
  4934.0 1710.31  4940.7 1711.98  4949.9 1712.39  4986.6 1711.19  4993.3 1711.83
  5011.3 1711.87  5020.1 1712.30  5320.5 1719.88  5405.0 1720.86  5454.4 1720.81
#Mann=10,-1,0
  4314.6    0.07       0  4341.4   0.035       0  4677.9    0.07       0
  4906.0   0.035       0  4923.5   0.035       0  4932.9   0.035       0
  5011.3    0.07       0  5020.1   0.035       0  5320.5    0.07       0
  5405.0   0.035       0
Bank Sta=4923.5,4932.9
Exp/Cntr=0.3,0.1

Type RM Length L Ch R = 1,2432,424,424,424
BEGIN DESCRIPTION:
Elm 01 47 2432.27
END DESCRIPTION:
XS GIS Cut Line= 3
      1562606.94      6860095.95      1562280.00      6859349.53
      1561851.25      6859004.06
#Sta/Elev= 30
  4195.3 1725.20  4216.5 1724.56  4231.7 1723.06  4247.7 1720.83  4257.8 1720.76
  4263.2 1722.32  4280.4 1720.35  4291.5 1719.77  4315.5 1718.66  4333.4 1717.04
  4399.6 1715.18  4542.4 1713.26  4575.2 1712.31  4688.0 1711.81  4758.1 1710.67
  4924.9 1712.13  4979.1 1711.80  4996.2 1709.85  4996.7 1709.35  5005.1 1709.35
  5005.6 1709.85  5021.8 1711.69  5029.4 1713.70  5042.6 1714.46  5115.5 1716.05
  5129.0 1716.78  5163.6 1717.17  5341.7 1720.23  5455.3 1720.88  5560.8 1720.47
#Mann=9,-1,0
  4195.3    0.05       0  4231.7    0.07       0  4291.5   0.035       0
  4399.6    0.07       0  4924.9   0.035       0  4996.2   0.035       0
  5005.6   0.035       0  5115.5    0.07       0  5163.6   0.035       0
Bank Sta=4996.2,5005.6
Exp/Cntr=0.3,0.1

Type RM Length L Ch R = 1,2008,297,297,297
BEGIN DESCRIPTION:
Elm 01 47 2008.22
END DESCRIPTION:
XS GIS Cut Line= 3
      1563076.14      6859981.78      1562558.76      6859384.53
      1561952.49      6858871.80
#Sta/Elev= 30
  4210.3 1722.38  4288.9 1720.71  4336.9 1719.06  4421.6 1716.14  4490.6 1714.44
  4629.8 1712.95  4851.4 1710.59  4879.9 1708.88  4908.4 1710.74  4957.8 1711.04
  4986.3 1710.02  4994.8 1708.14  4995.3 1707.64  5003.8 1707.64  5004.3 1708.14
  5007.4 1710.00  5015.2 1709.16  5021.7 1710.69  5149.5 1711.35  5199.7 1712.19
  5206.3 1713.01  5221.0 1712.71  5319.7 1716.10  5390.9 1717.28  5426.0 1718.54
  5511.8 1719.63  5624.9 1720.19  5745.8 1719.80  5760.1 1720.22  5794.5 1719.68
#Mann=8,-1,0
  4210.3   0.045       0  4288.9    0.05       0  4336.9   0.045       0
  4421.6    0.05       0  4629.8    0.07       0  4994.8    0.07       0
  5004.3    0.07       0  5221.0   0.035       0
Bank Sta=4994.8,5004.3
Exp/Cntr=0.3,0.1

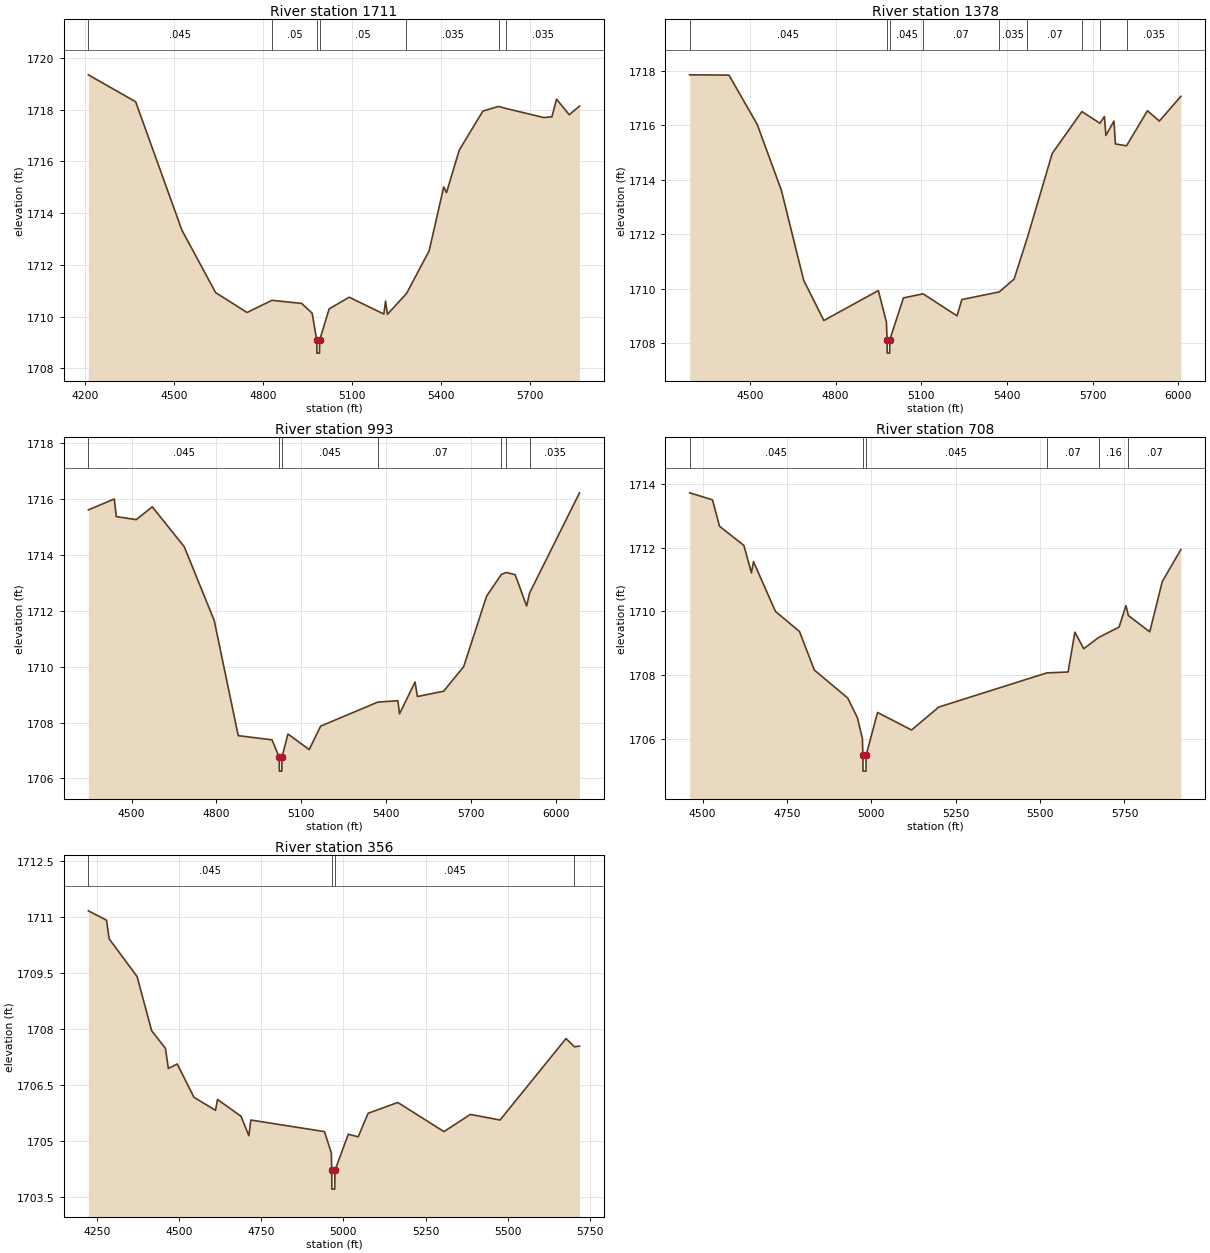
Type RM Length L Ch R = 1,1711,333,333,333
BEGIN DESCRIPTION:
Elm 01 47 1710.95
END DESCRIPTION:
XS GIS Cut Line= 3
      1563346.98      6859801.23      1562822.65      6859245.64
      1562062.23      6858783.84
#Sta/Elev= 30
  4212.5 1719.34  4371.7 1718.30  4527.5 1713.34  4640.8 1710.93  4746.8 1710.16
  4830.5 1710.63  4930.8 1710.51  4966.0 1710.13  4981.5 1709.09  4982.0 1708.59
  4990.7 1708.59  4991.2 1709.09  5023.2 1710.30  5090.7 1710.75  5207.3 1710.10
  5213.1 1710.60  5219.4 1710.09  5283.6 1710.89  5359.8 1712.54  5408.9 1715.01
  5418.3 1714.79  5461.2 1716.43  5540.7 1717.94  5593.4 1718.12  5618.6 1718.04
  5745.9 1717.69  5773.3 1717.72  5788.7 1718.40  5831.4 1717.80  5866.1 1718.13
#Mann=7,-1,0
  4212.5   0.045       0  4830.5    0.05       0  4981.5    0.07       0
  4991.2    0.05       0  5283.6   0.035       0  5593.4    0.07       0
  5618.6   0.035       0
Bank Sta=4981.5,4991.2
Exp/Cntr=0.3,0.1

Type RM Length L Ch R = 1,1378,385,385,385
BEGIN DESCRIPTION:
Elm 01 47 1377.51
END DESCRIPTION:
XS GIS Cut Line= 3
      1563541.38      6859506.04      1563044.87      6859002.59
      1562072.69      6858717.88
#Sta/Elev= 30
  4289.2 1717.86  4426.7 1717.85  4525.6 1716.04  4610.5 1713.61  4688.3 1710.31
  4759.0 1708.83  4949.9 1709.93  4978.2 1708.77  4980.5 1708.13  4981.0 1707.63
  4989.7 1707.63  4990.2 1708.13  5037.8 1709.66  5106.8 1709.81  5225.4 1709.00
  5242.5 1709.60  5373.3 1709.88  5425.2 1710.35  5472.2 1711.89  5558.8 1714.97
  5662.7 1716.51  5725.9 1716.08  5741.6 1716.33  5746.8 1715.63  5775.0 1716.16
  5780.2 1715.32  5819.0 1715.25  5892.3 1716.54  5934.0 1716.16  6009.3 1717.07
#Mann=9,-1,0
  4289.2   0.045       0  4980.5   0.045       0  4990.2   0.045       0
  5106.8    0.07       0  5373.3   0.035       0  5472.2    0.07       0
  5662.7   0.035       0  5725.9    0.07       0  5819.0   0.035       0
Bank Sta=4980.5,4990.2
Exp/Cntr=0.3,0.1

Type RM Length L Ch R = 1,993,285,285,285
BEGIN DESCRIPTION:
Elm 01 47 992.74
END DESCRIPTION:
XS GIS Cut Line= 3
      1563805.27      6859207.43      1563343.48      6858763.01
      1562260.13      6858596.34
#Sta/Elev= 30
  4347.3 1715.61  4439.1 1716.00  4446.0 1715.37  4516.7 1715.26  4573.3 1715.72
  4686.5 1714.29  4792.5 1711.65  4877.4 1707.53  4996.8 1707.38  5022.3 1706.76
  5022.8 1706.26  5031.5 1706.26  5032.0 1706.76  5053.2 1707.59  5128.3 1707.03
  5168.8 1707.87  5370.8 1708.73  5442.0 1708.78  5447.8 1708.31  5502.7 1709.45
  5511.0 1708.93  5603.8 1709.12  5674.7 1710.00  5755.6 1712.52  5807.9 1713.30
  5825.8 1713.37  5856.8 1713.29  5897.3 1712.17  5907.6 1712.63  6084.3 1716.22
#Mann=7,-1,0
  4347.3   0.045       0  5022.3   0.045       0  5032.0   0.045       0
  5370.8    0.07       0  5807.9   0.035       0  5825.8    0.07       0
  5907.6   0.035       0
Bank Sta=5022.3,5032
Exp/Cntr=0.3,0.1

Type RM Length L Ch R = 1,708,352,352,352
BEGIN DESCRIPTION:
Elm 01 47 708.32
END DESCRIPTION:
XS GIS Cut Line= 3
      1563819.19      6858978.31      1563506.68      6858544.26
      1562593.53      6858426.21
#Sta/Elev= 30
  4461.6 1713.72  4529.2 1713.50  4550.1 1712.67  4622.2 1712.07  4644.6 1711.21
  4650.7 1711.56  4715.8 1710.00  4787.0 1709.37  4831.1 1708.16  4930.2 1707.28
  4958.8 1706.66  4973.5 1706.01  4974.8 1705.49  4975.3 1704.99  4984.0 1704.99
  4984.5 1705.49  5018.3 1706.83  5119.1 1706.28  5199.8 1707.00  5519.4 1708.07
  5583.0 1708.10  5603.1 1709.35  5629.3 1708.83  5673.3 1709.18  5734.2 1709.51
  5754.4 1710.18  5761.8 1709.87  5825.0 1709.36  5862.2 1710.94  5917.2 1711.94
#Mann=6,-1,0
  4461.6   0.045       0  4974.8   0.045       0  4984.5   0.045       0
  5519.4    0.07       0  5673.3    0.16       0  5761.8    0.07       0
Bank Sta=4974.8,4984.5
Exp/Cntr=0.3,0.1

Type RM Length L Ch R = 1,356,0,0,0
BEGIN DESCRIPTION:
Elm 01 47 355.64
END DESCRIPTION:
XS GIS Cut Line= 3
      1564180.29      6858940.09      1563740.07      6858301.90
      1563024.08      6858245.65
#Sta/Elev= 30
  4224.7 1711.16  4280.0 1710.91  4288.0 1710.41  4373.0 1709.40  4417.2 1707.95
  4459.1 1707.48  4468.0 1706.94  4495.0 1707.06  4545.7 1706.17  4611.3 1705.82
  4617.4 1706.11  4689.0 1705.66  4712.7 1705.14  4718.8 1705.56  4942.6 1705.25
  4963.6 1704.68  4964.7 1704.21  4965.2 1703.71  4974.0 1703.71  4974.5 1704.21
  5015.1 1705.18  5045.2 1705.11  5075.3 1705.74  5165.6 1706.03  5306.0 1705.25
  5386.3 1705.71  5476.5 1705.56  5677.1 1707.74  5702.9 1707.52  5718.2 1707.54
#Mann=4,-1,0
  4224.7   0.045       0  4964.7   0.045       0  4974.5   0.045       0
  5702.9    0.07       0
Bank Sta=4964.7,4974.5
Exp/Cntr=0.3,0.1

Chan Stop Cuts=-1