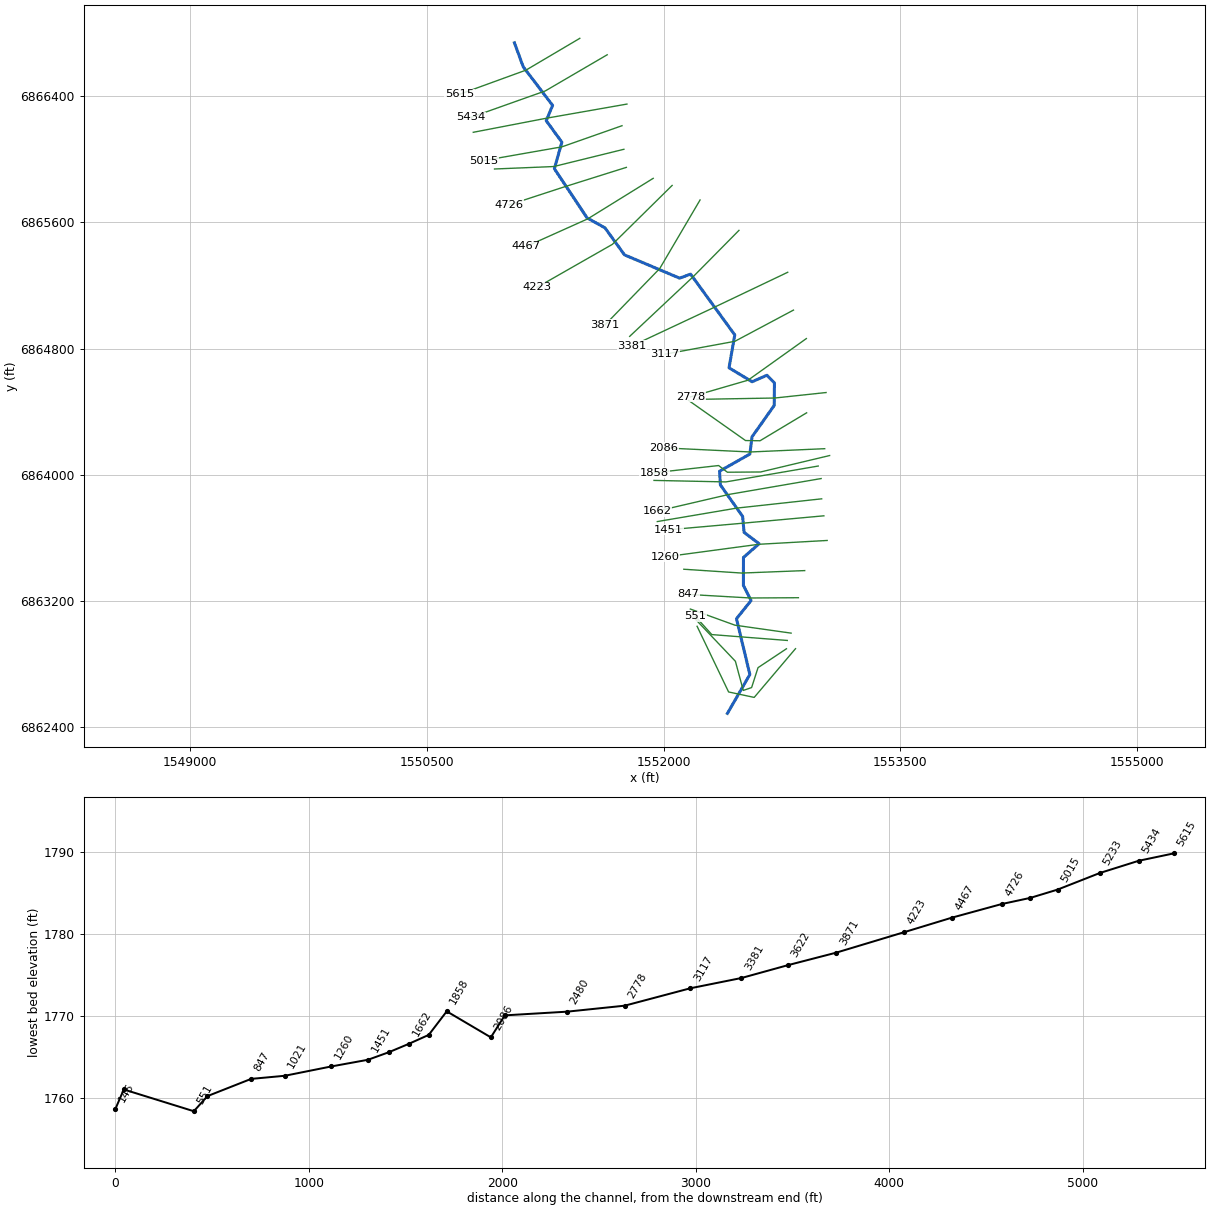
--- Elm 01 48.prj (project) ---

Proj Title=Elm 01 48 Base Level Engineering
Current Plan=p01
Default Exp/Contr=0.3,0.1
English Units
Geom File=g01
Flow File=f01
Plan File=p01
BEGIN DESCRIPTION:
Elm 01 48
END DESCRIPTION:

--- Elm 01 48.p01 (plan) ---

Plan Title=Multiple Run
Short Identifier=Multiple
Geom File=g01
Flow File=f01
Subcritical Flow
K Sum by GR= 0
Std Step Tol= 0.01
Critical Tol= 0.01
Num of Std Step Trials= 20
Max Error Tol= 0.3
Flow Tol Ratio= 0.001
Split Flow NTrial= 30
Split Flow Tol= 0.02
Split Flow Ratio= 0.02
Log Output Level= 0
Friction Slope Method= 1
Unsteady Friction Slope Method= 2
Unsteady Bridges Friction Slope Method= 1
Parabolic Critical Depth
Global Vel Dist=  1 , 1 , 1
Global Log Level= 0
CheckData=True
Encroach Param= -1, 0, 0, 0
BEGIN DESCRIPTION:
Multiple Run
END DESCRIPTION:

--- Elm 01 48.f01 (steady flow) ---

Flow Title=Multiple
Number of Profiles=7
Profile Names=10-year,25-year,50-year,1pct_min,100-year,1pct_plu,500-year
River Rch & RM= Elm 01 48,Reach-1,5615
     117     154     182     135     216     297     306
Boundary for River Rch & Prof#=Elm 01 48,Reach-1,1
Up Type=0
Dn Type=3
Dn Slope=0.005
Boundary for River Rch & Prof#=Elm 01 48,Reach-1,2
Up Type=0
Dn Type=3
Dn Slope=0.005
Boundary for River Rch & Prof#=Elm 01 48,Reach-1,3
Up Type=0
Dn Type=3
Dn Slope=0.005
Boundary for River Rch & Prof#=Elm 01 48,Reach-1,4
Up Type=0
Dn Type=3
Dn Slope=0.005
Boundary for River Rch & Prof#=Elm 01 48,Reach-1,5
Up Type=0
Dn Type=3
Dn Slope=0.005
Boundary for River Rch & Prof#=Elm 01 48,Reach-1,6
Up Type=0
Dn Type=3
Dn Slope=0.005
Boundary for River Rch & Prof#=Elm 01 48,Reach-1,7
Up Type=0
Dn Type=3
Dn Slope=0.005

--- Elm 01 48.g01 (geometry) ---

Geom Title=Existing Conditions

River Reach=Elm 01 48,Reach-1
Reach XY= 30
      1551055.00      6866738.00      1551110.82      6866585.69
      1551296.93      6866341.31      1551256.67      6866244.05
      1551355.67      6866108.08      1551308.34      6865939.72
      1551515.65      6865628.01      1551628.83      6865565.14
      1551752.69      6865393.82      1552101.77      6865246.25
      1552171.70      6865271.63      1552451.54      6864886.50
      1552415.06      6864678.00      1552561.13      6864589.84
      1552655.33      6864630.75      1552702.96      6864582.55
      1552701.46      6864439.47      1552560.77      6864240.32
      1552547.27      6864131.50      1552355.18      6864022.92
      1552360.41      6863935.58      1552501.17      6863736.41
      1552510.46      6863635.34      1552605.64      6863563.00
      1552506.65      6863476.17      1552506.24      6863298.50
      1552555.04      6863203.34      1552462.33      6863088.10
      1552547.19      6862734.59      1552405.00      6862488.00

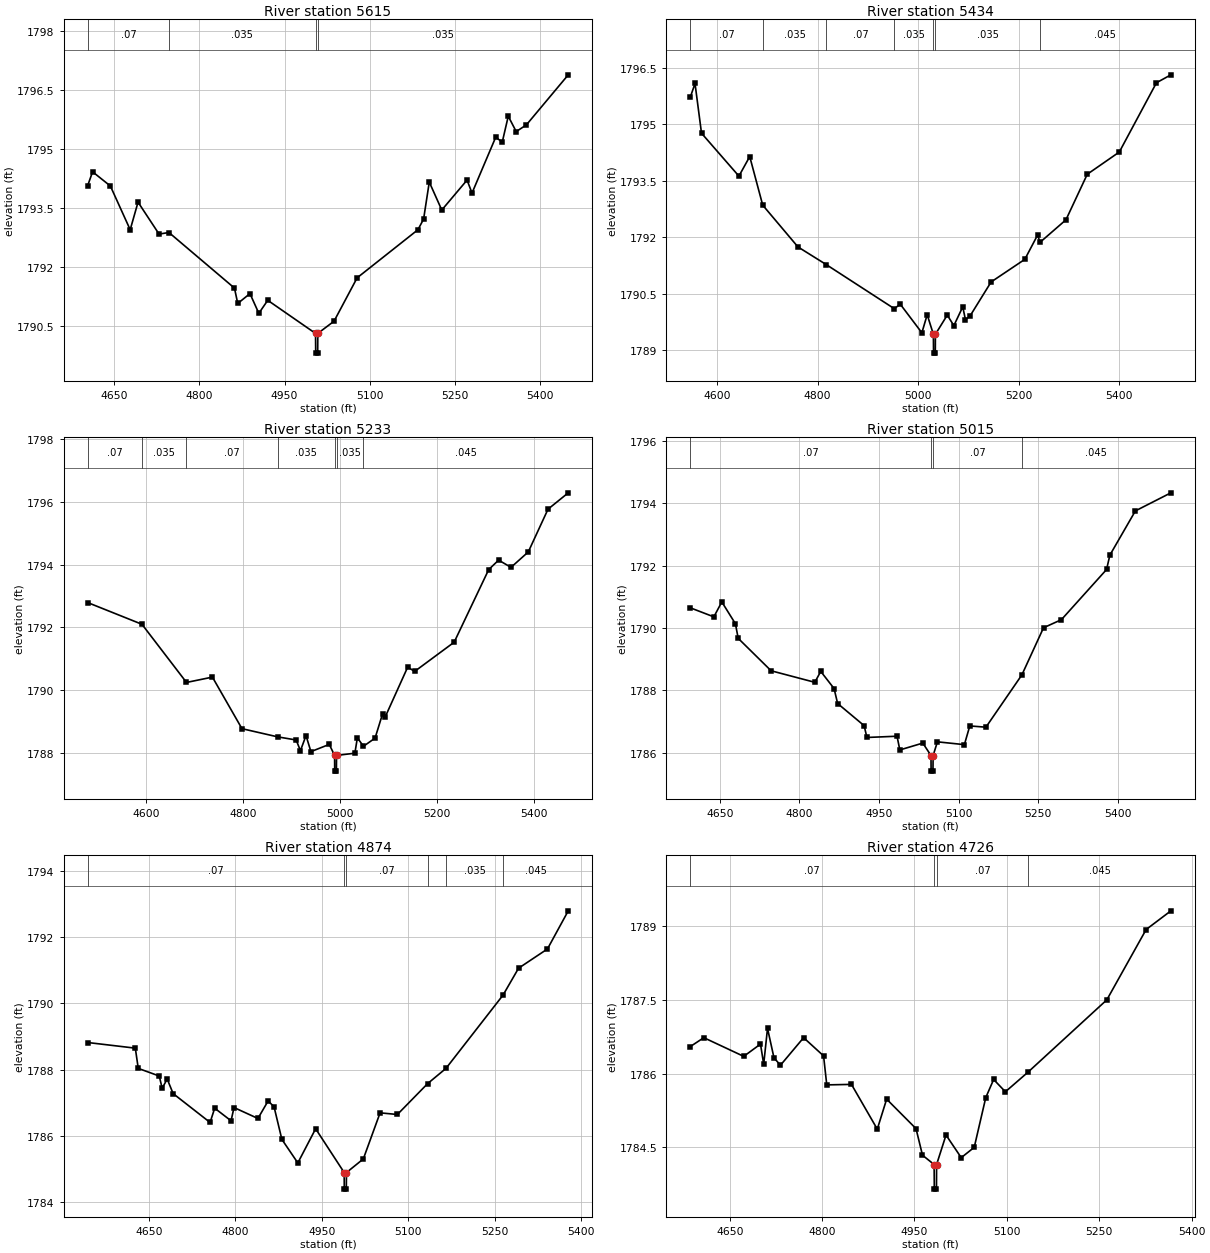
Type RM Length L Ch R = 1,5615,181,181,181
BEGIN DESCRIPTION:
Elm 01 48 5614.673
END DESCRIPTION:
XS GIS Cut Line= 3
      1551469.41      6866766.17      1551128.01      6866564.53
      1550705.76      6866411.00
#Sta/Elev= 30
  4603.5 1794.07  4612.1 1794.42  4643.4 1794.06  4678.3 1792.95  4692.1 1793.65
  4729.1 1792.84  4746.5 1792.88  4861.8 1791.47  4867.6 1791.08  4889.1 1791.33
  4904.7 1790.83  4920.4 1791.16  5004.5 1790.32  5004.8 1789.82  5008.3 1789.82
  5008.5 1790.32  5037.1 1790.63  5077.7 1791.73  5184.7 1792.95  5194.7 1793.22
  5204.7 1794.16  5226.7 1793.45  5271.2 1794.21  5279.9 1793.88  5321.7 1795.30
  5333.1 1795.17  5343.7 1795.83  5357.7 1795.44  5375.6 1795.61  5449.3 1796.88
#Mann=4,-1,0
  4603.5    0.07       0  4746.5   0.035       0  5004.5   0.035       0
  5008.5   0.035       0
Bank Sta=5004.5,5008.5
Exp/Cntr=0.3,0.1

Type RM Length L Ch R = 1,5434,201,201,201
BEGIN DESCRIPTION:
Elm 01 48 5433.78
END DESCRIPTION:
XS GIS Cut Line= 3
      1551643.00      6866661.98      1551250.67      6866432.84
      1550778.34      6866265.02
#Sta/Elev= 30
  4546.9 1795.72  4556.2 1796.08  4569.1 1794.76  4643.5 1793.62  4665.0 1794.14
  4690.8 1792.85  4760.9 1791.74  4817.3 1791.27  4952.5 1790.10  4964.3 1790.22
  5007.3 1789.46  5017.9 1789.94  5030.2 1789.42  5030.5 1788.92  5034.0 1788.92
  5034.2 1789.42  5057.8 1789.93  5070.9 1789.65  5088.6 1790.15  5093.9 1789.81
  5102.8 1789.90  5145.0 1790.81  5212.0 1791.41  5237.6 1792.06  5242.1 1791.86
  5293.8 1792.46  5336.2 1793.67  5399.9 1794.26  5473.8 1796.10  5502.5 1796.31
#Mann=7,-1,0
  4546.9    0.07       0  4690.8   0.035       0  4817.3    0.07       0
  4952.5   0.035       0  5030.2   0.035       0  5034.2   0.035       0
  5242.1   0.045       0
Bank Sta=5030.2,5034.2
Exp/Cntr=0.3,0.1

Type RM Length L Ch R = 1,5233,218,218,218
BEGIN DESCRIPTION:
Elm 01 48 5232.65
END DESCRIPTION:
XS GIS Cut Line= 3
      1551768.08      6866349.51      1551254.14      6866259.23
      1550794.09      6866170.69
#Sta/Elev= 30
  4479.5 1792.79  4591.3 1792.10  4683.1 1790.25  4736.5 1790.42  4797.4 1788.78
  4870.9 1788.52  4909.1 1788.42  4917.9 1788.08  4929.4 1788.56  4939.5 1788.05
  4977.3 1788.28  4988.3 1787.93  4988.5 1787.43  4992.0 1787.43  4992.3 1787.93
  5030.1 1788.00  5035.2 1788.49  5047.8 1788.22  5071.7 1788.48  5087.1 1789.25
  5092.2 1789.14  5139.0 1790.74  5153.2 1790.60  5234.7 1791.53  5305.9 1793.84
  5326.3 1794.14  5351.8 1793.91  5387.4 1794.40  5428.1 1795.76  5469.8 1796.28
#Mann=7,-1,0
  4479.5    0.07       0  4591.3   0.035       0  4683.1    0.07       0
  4870.9   0.035       0  4988.3   0.035       0  4992.3   0.035       0
  5047.8   0.045       0
Bank Sta=4988.3,4992.3
Exp/Cntr=0.3,0.1

Type RM Length L Ch R = 1,5015,141,141,141
BEGIN DESCRIPTION:
Elm 01 48 5014.53
END DESCRIPTION:
XS GIS Cut Line= 3
      1551736.79      6866212.36      1551356.58      6866078.67
      1550861.76      6865991.86
#Sta/Elev= 30
  4594.7 1790.65  4639.0 1790.36  4654.0 1790.84  4679.6 1790.14  4684.9 1789.67
  4746.9 1788.63  4829.2 1788.26  4840.4 1788.61  4865.5 1788.06  4872.2 1787.58
  4922.1 1786.87  4927.4 1786.49  4984.1 1786.53  4989.4 1786.09  5032.7 1786.31
  5048.1 1785.91  5048.3 1785.41  5051.8 1785.41  5052.1 1785.91  5060.2 1786.35
  5111.0 1786.26  5121.2 1786.86  5151.6 1786.82  5219.4 1788.50  5260.1 1790.01
  5293.8 1790.27  5378.9 1791.88  5385.1 1792.34  5433.2 1793.76  5500.1 1794.34
#Mann=4,-1,0
  4594.7    0.07       0  5048.1    0.07       0  5052.1    0.07       0
  5219.4   0.045       0
Bank Sta=5048.1,5052.1
Exp/Cntr=0.3,0.1

Type RM Length L Ch R = 1,4874,148,148,148
BEGIN DESCRIPTION:
Elm 01 48 4874.45
END DESCRIPTION:
XS GIS Cut Line= 3
      1551748.92      6866063.04      1551304.49      6865953.67
      1550928.90      6865938.10
#Sta/Elev= 30
  4543.9 1788.82  4626.5 1788.65  4631.6 1788.04  4668.0 1787.81  4673.1 1787.44
  4681.8 1787.72  4692.1 1787.28  4756.2 1786.41  4764.2 1786.84  4792.6 1786.46
  4797.7 1786.86  4839.2 1786.53  4856.9 1787.06  4867.2 1786.88  4880.7 1785.90
  4908.4 1785.19  4939.3 1786.22  4988.8 1784.90  4989.0 1784.40  4992.5 1784.40
  4992.8 1784.90  5022.0 1785.31  5051.1 1786.70  5081.1 1786.65  5133.5 1787.58
  5165.4 1788.04  5264.4 1790.25  5291.3 1791.06  5341.4 1791.64  5377.5 1792.79
#Mann=6,-1,0
  4543.9    0.07       0  4988.8    0.07       0  4992.8    0.07       0
  5133.5   0.045       0  5165.4   0.035       0  5264.4   0.045       0
Bank Sta=4988.8,4992.8
Exp/Cntr=0.3,0.1

Type RM Length L Ch R = 1,4726,259,259,259
BEGIN DESCRIPTION:
Elm 01 48 4725.65
END DESCRIPTION:
XS GIS Cut Line= 3
      1551764.52      6865948.45      1551366.99      6865823.46
      1551021.47      6865710.61
#Sta/Elev= 30
  4586.1 1786.55  4608.0 1786.73  4672.8 1786.35  4700.0 1786.60  4705.2 1786.19
  4711.4 1786.92  4721.9 1786.32  4732.4 1786.17  4770.0 1786.73  4802.4 1786.36
  4807.6 1785.77  4847.7 1785.78  4889.6 1784.87  4904.8 1785.48  4952.5 1784.88
  4963.0 1784.34  4981.9 1784.15  4982.2 1783.65  4985.7 1783.65  4985.9 1784.15
  5001.2 1784.75  5025.9 1784.29  5047.0 1784.50  5065.7 1785.51  5078.5 1785.88
  5097.6 1785.63  5134.4 1786.03  5262.3 1787.50  5326.1 1788.93  5366.3 1789.31
#Mann=4,-1,0
  4586.1    0.07       0  4981.9    0.07       0  4985.9    0.07       0
  5134.4   0.045       0
Bank Sta=4981.9,4985.9
Exp/Cntr=0.3,0.1

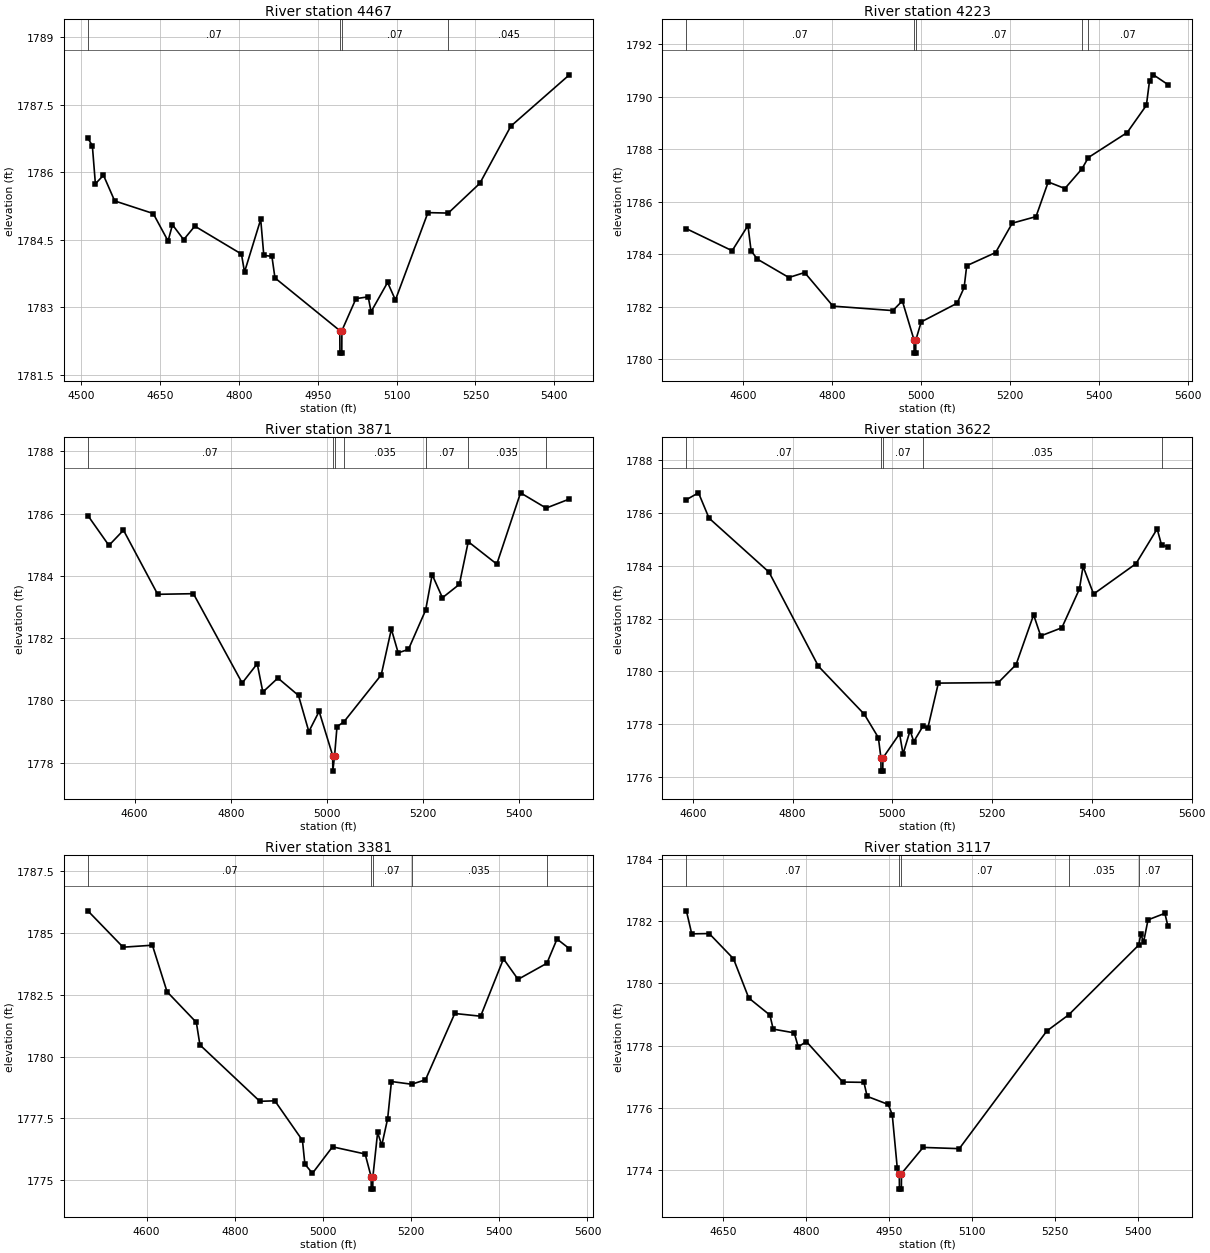
Type RM Length L Ch R = 1,4467,244,244,244
BEGIN DESCRIPTION:
Elm 01 48 4466.74
END DESCRIPTION:
XS GIS Cut Line= 3
      1551934.69      6865879.01      1551519.77      6865622.08
      1551129.61      6865446.94
#Sta/Elev= 30
  4513.0 1786.75  4521.5 1786.59  4527.3 1785.74  4542.7 1785.93  4564.0 1785.36
  4637.3 1785.08  4665.5 1784.47  4673.9 1784.83  4695.2 1784.50  4716.4 1784.80
  4805.1 1784.18  4810.9 1783.78  4841.7 1784.95  4847.6 1784.15  4863.0 1784.13
  4868.8 1783.65  4992.1 1782.48  4992.4 1781.98  4995.9 1781.98  4996.1 1782.48
  5022.9 1783.19  5046.1 1783.23  5051.6 1782.90  5083.0 1783.55  5097.9 1783.16
  5159.7 1785.10  5198.4 1785.09  5258.4 1785.75  5317.4 1787.02  5428.7 1788.16
#Mann=4,-1,0
  4513.0    0.07       0  4992.1    0.07       0  4996.1    0.07       0
  5198.4   0.045       0
Bank Sta=4992.1,4996.1
Exp/Cntr=0.3,0.1

Type RM Length L Ch R = 1,4223,352,352,352
BEGIN DESCRIPTION:
Elm 01 48 4223.28
END DESCRIPTION:
XS GIS Cut Line= 3
      1552054.46      6865833.85      1551676.02      6865460.62
      1551199.27      6865188.44
#Sta/Elev= 30
  4473.5 1784.97  4576.2 1784.13  4611.7 1785.09  4618.7 1784.13  4632.8 1783.81
  4703.5 1783.11  4738.9 1783.30  4802.5 1782.02  4936.8 1781.85  4958.1 1782.22
  4984.4 1780.73  4984.6 1780.23  4988.1 1780.23  4988.4 1780.73  5000.5 1781.42
  5081.0 1782.13  5096.8 1782.73  5102.6 1783.56  5167.4 1784.06  5204.8 1785.18
  5258.1 1785.43  5285.5 1786.75  5322.9 1786.50  5361.2 1787.25  5375.6 1787.68
  5462.6 1788.63  5505.8 1789.67  5512.9 1790.61  5521.6 1790.83  5554.0 1790.46
#Mann=5,-1,0
  4473.5    0.07       0  4984.4    0.07       0  4988.4    0.07       0
  5361.2   0.045       0  5375.6    0.07       0
Bank Sta=4984.4,4988.4
Exp/Cntr=0.3,0.1

Type RM Length L Ch R = 1,3871,249,249,249
BEGIN DESCRIPTION:
Elm 01 48 3871.32
END DESCRIPTION:
XS GIS Cut Line= 3
      1552231.56      6865741.83      1551976.37      6865307.84
      1551629.16      6864950.22
#Sta/Elev= 30
  4502.6 1785.94  4546.4 1784.98  4576.7 1785.47  4647.9 1783.41  4722.2 1783.43
  4823.7 1780.56  4855.0 1781.18  4866.7 1780.27  4898.0 1780.72  4940.9 1780.16
  4962.4 1779.00  4983.8 1779.65  5012.0 1778.23  5012.3 1777.73  5016.0 1778.23
  5021.0 1779.16  5035.2 1779.31  5113.0 1780.82  5134.1 1782.29  5148.3 1781.53
  5169.6 1781.64  5205.4 1782.90  5219.0 1784.04  5240.4 1783.30  5275.6 1783.73
  5294.1 1785.10  5353.5 1784.38  5402.9 1786.67  5456.1 1786.18  5504.5 1786.47
#Mann=7,-1,0
  4502.6    0.07       0  5012.0    0.07       0  5016.0    0.07       0
  5035.2   0.035       0  5205.4    0.07       0  5294.1   0.035       0
  5456.1   0.045       0
Bank Sta=5012,5016
Exp/Cntr=0.3,0.1

Type RM Length L Ch R = 1,3622,241,241,241
BEGIN DESCRIPTION:
Elm 01 48 3622.14
END DESCRIPTION:
XS GIS Cut Line= 3
      1552478.13      6865549.18      1552188.17      6865255.76
      1551785.40      6864877.29
#Sta/Elev= 30
  4587.1 1786.51  4611.4 1786.77  4632.5 1785.81  4752.8 1783.76  4851.8 1780.19
  4943.7 1778.37  4972.0 1777.48  4977.1 1776.71  4977.3 1776.21  4980.8 1776.21
  4981.1 1776.71  5014.5 1777.63  5021.4 1776.86  5035.6 1777.75  5042.9 1777.33
  5061.8 1777.93  5071.2 1777.85  5092.2 1779.55  5212.4 1779.57  5248.0 1780.25
  5283.2 1782.14  5297.4 1781.34  5339.8 1781.65  5375.0 1783.12  5382.3 1783.98
  5403.4 1782.93  5488.3 1784.08  5530.8 1785.40  5539.8 1784.78  5552.3 1784.73
#Mann=5,-1,0
  4587.1    0.07       0  4977.1    0.07       0  4981.1    0.07       0
  5061.8   0.035       0  5539.8    0.07       0
Bank Sta=4977.1,4981.1
Exp/Cntr=0.3,0.1

Type RM Length L Ch R = 1,3381,264,264,264
BEGIN DESCRIPTION:
Elm 01 48 3380.71
END DESCRIPTION:
XS GIS Cut Line= 3
      1552787.13      6865283.53      1552302.76      6865052.63
      1551799.63      6864816.68
#Sta/Elev= 30
  4466.6 1785.89  4546.5 1784.42  4613.0 1784.50  4646.2 1782.62  4712.7 1781.38
  4720.8 1780.47  4856.7 1778.19  4890.8 1778.21  4953.4 1776.61  4958.9 1775.65
  4976.1 1775.28  5021.6 1776.35  5095.6 1776.06  5109.2 1775.14  5109.4 1774.64
  5112.9 1774.64  5113.2 1775.14  5123.9 1776.93  5133.3 1776.41  5146.7 1777.49
  5155.3 1778.99  5201.1 1778.88  5232.5 1779.06  5298.9 1781.74  5357.6 1781.63
  5409.4 1783.95  5442.5 1783.12  5507.9 1783.77  5530.9 1784.75  5558.9 1784.36
#Mann=5,-1,0
  4466.6    0.07       0  5109.2    0.07       0  5113.2    0.07       0
  5201.1   0.035       0  5507.9    0.07       0
Bank Sta=5109.2,5113.2
Exp/Cntr=0.3,0.1

Type RM Length L Ch R = 1,3117,339,339,339
BEGIN DESCRIPTION:
Elm 01 48 3117.33
END DESCRIPTION:
XS GIS Cut Line= 3
      1552823.55      6865043.93      1552452.06      6864846.03
      1552009.72      6864764.50
#Sta/Elev= 30
  4583.0 1782.33  4592.7 1781.59  4624.3 1781.60  4668.2 1780.79  4695.8 1779.53
  4734.1 1778.98  4740.0 1778.53  4778.0 1778.41  4785.3 1777.96  4800.0 1778.13
  4865.9 1776.83  4904.1 1776.82  4909.9 1776.37  4948.1 1776.11  4955.3 1775.78
  4964.4 1774.06  4968.0 1773.89  4968.3 1773.39  4971.8 1773.39  4972.0 1773.89
  5011.1 1774.73  5076.5 1774.69  5234.8 1778.47  5274.4 1778.99  5401.0 1781.23
  5404.7 1781.58  5409.8 1781.33  5417.8 1782.04  5448.3 1782.25  5453.7 1781.84
#Mann=5,-1,0
  4583.0    0.07       0  4968.0    0.07       0  4972.0    0.07       0
  5274.4   0.035       0  5401.0    0.07       0
Bank Sta=4968,4972
Exp/Cntr=0.3,0.1

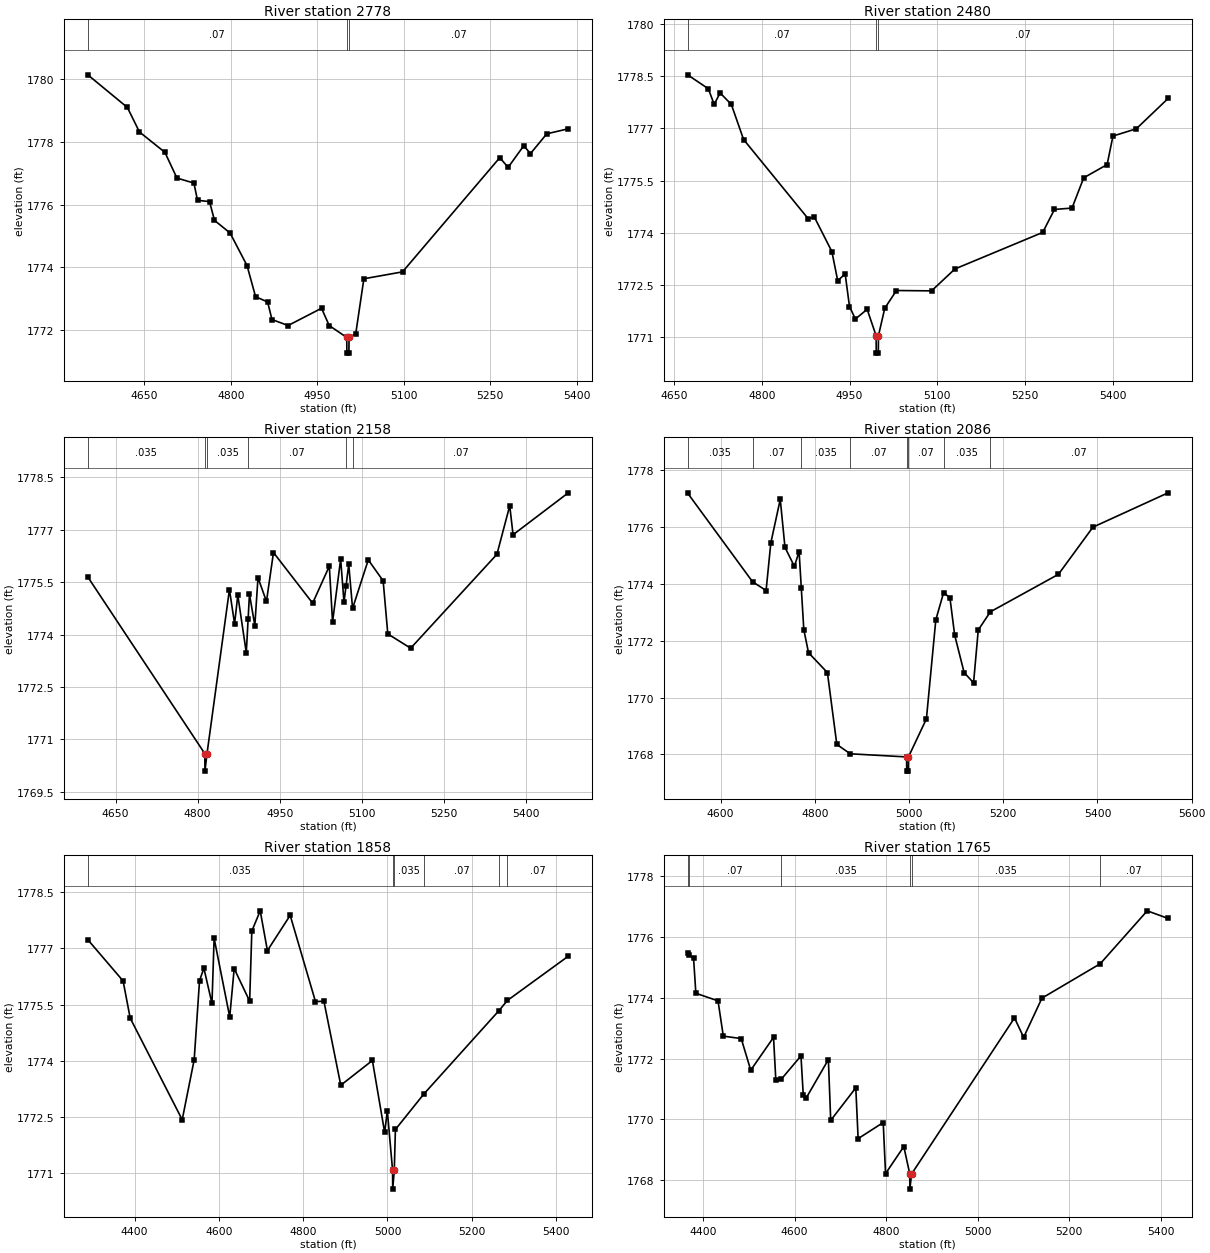
Type RM Length L Ch R = 1,2778,298,298,298
BEGIN DESCRIPTION:
Elm 01 48 2778.42
END DESCRIPTION:
XS GIS Cut Line= 3
      1552905.21      6864863.41      1552535.39      6864599.51
      1552170.79      6864493.60
#Sta/Elev= 30
  4551.7 1780.14  4620.4 1779.10  4641.3 1778.32  4685.5 1777.67  4706.4 1776.85
  4735.9 1776.69  4742.1 1776.14  4763.0 1776.10  4771.6 1775.50  4798.6 1775.10
  4828.1 1774.06  4842.9 1773.07  4863.8 1772.90  4871.4 1772.34  4899.4 1772.15
  4957.4 1772.70  4970.7 1772.15  5001.2 1771.77  5001.4 1771.27  5004.9 1771.27
  5005.2 1771.77  5016.8 1771.89  5030.9 1773.64  5098.0 1773.86  5266.8 1777.50
  5281.3 1777.19  5308.4 1777.88  5320.1 1777.63  5348.4 1778.26  5385.7 1778.42
#Mann=3,-1,0
  4551.7    0.07       0  5001.2    0.07       0  5005.2    0.07       0
Bank Sta=5001.2,5005.2
Exp/Cntr=0.3,0.1

Type RM Length L Ch R = 1,2480,322,322,322
BEGIN DESCRIPTION:
Elm 01 48 2479.86
END DESCRIPTION:
XS GIS Cut Line= 3
      1553030.15      6864521.38      1552705.53      6864486.66
      1552210.78      6864477.98
#Sta/Elev= 30
  4673.2 1778.54  4708.6 1778.14  4718.6 1777.69  4728.7 1778.02  4747.9 1777.69
  4768.9 1776.68  4879.5 1774.40  4889.6 1774.46  4919.8 1773.46  4929.8 1772.62
  4942.5 1772.82  4949.9 1771.88  4960.0 1771.52  4980.1 1771.80  4995.4 1771.04
  4995.7 1770.54  4999.2 1770.54  4999.4 1771.04  5010.2 1771.83  5030.2 1772.34
  5090.2 1772.33  5130.2 1772.96  5280.2 1774.01  5300.3 1774.67  5330.3 1774.71
  5350.3 1775.58  5390.3 1775.96  5400.3 1776.78  5440.3 1776.99  5494.5 1777.86
#Mann=3,-1,0
  4673.2    0.07       0  4995.4    0.07       0  4999.4    0.07       0
Bank Sta=4995.4,4999.4
Exp/Cntr=0.3,0.1

Type RM Length L Ch R = 1,2158,72,72,72
BEGIN DESCRIPTION:
Elm 01 48 2158.19
END DESCRIPTION:
XS GIS Cut Line= 4
      1552906.96      6864392.93      1552611.78      6864215.83
      1552519.67      6864217.12      1552158.43      6864471.71
#Sta/Elev= 30
  4599.2 1775.65  4813.1 1770.59  4813.3 1770.09  4817.1 1770.59  4858.1 1775.29
  4867.5 1774.31  4873.4 1775.13  4888.9 1773.48  4892.3 1774.46  4894.7 1775.16
  4904.5 1774.26  4910.3 1775.63  4925.8 1774.95  4938.6 1776.35  5010.2 1774.90
  5040.7 1775.96  5046.6 1774.36  5061.4 1776.16  5067.5 1774.93  5071.2 1775.39
  5076.2 1776.01  5083.2 1774.75  5111.9 1776.14  5139.1 1775.54  5147.6 1774.02
  5189.4 1773.61  5347.1 1776.30  5370.5 1777.69  5376.6 1776.86  5477.5 1778.06
#Mann=6,-1,0
  4599.2   0.035       0  4813.1    0.07       0  4817.1   0.035       0
  4892.3    0.07       0  5071.2   0.035       0  5083.2    0.07       0
Bank Sta=4813.1,4817.1
Exp/Cntr=0.3,0.1

Type RM Length L Ch R = 1,2086,228,228,228
BEGIN DESCRIPTION:
Elm 01 48 2085.86
END DESCRIPTION:
XS GIS Cut Line= 3
      1553021.48      6864165.48      1552549.28      6864144.64
      1552002.46      6864170.68
#Sta/Elev= 30
  4529.8 1777.20  4667.6 1774.08  4696.4 1773.77  4706.5 1775.45  4726.5 1776.98
  4736.5 1775.29  4756.5 1774.62  4766.5 1775.14  4771.2 1773.85  4776.5 1772.39
  4786.5 1771.58  4826.6 1770.88  4846.6 1768.35  4875.2 1768.02  4994.7 1767.91
  4995.0 1767.41  4998.5 1767.41  4998.7 1767.91  5036.8 1769.25  5056.8 1772.74
  5073.4 1773.70  5086.8 1773.51  5096.8 1772.20  5116.9 1770.88  5136.9 1770.52
  5146.9 1772.38  5172.6 1773.02  5317.1 1774.34  5390.3 1776.00  5549.9 1777.21
#Mann=8,-1,0
  4529.8   0.035       0  4667.6    0.07       0  4771.2   0.035       0
  4875.2    0.07       0  4994.7    0.07       0  4998.7    0.07       0
  5073.4   0.035       0  5172.6    0.07       0
Bank Sta=4994.7,4998.7
Exp/Cntr=0.3,0.1

Type RM Length L Ch R = 1,1858,93,93,93
BEGIN DESCRIPTION:
Elm 01 48 1788.62
END DESCRIPTION:
XS GIS Cut Line= 5
      1553052.78      6864122.08      1552615.26      6864017.91
      1552404.72      6864016.34      1552349.11      6864058.72
      1551942.29      6864012.96
#Sta/Elev= 30
  4289.2 1777.23  4372.9 1776.13  4389.7 1775.14  4513.1 1772.43  4541.5 1774.03
  4554.2 1776.14  4564.5 1776.47  4583.7 1775.53  4588.8 1777.27  4625.8 1775.17
  4636.4 1776.46  4673.1 1775.59  4678.2 1777.46  4698.1 1778.00  4715.2 1776.94
  4769.2 1777.88  4829.2 1775.58  4849.2 1775.59  4889.2 1773.35  4964.2 1774.01
  4993.3 1772.09  4999.6 1772.67  5012.1 1771.08  5012.4 1770.58  5016.1 1771.08
  5018.8 1772.17  5085.8 1773.11  5264.5 1775.34  5284.4 1775.61  5428.8 1776.79
#Mann=6,-1,0
  4289.2   0.035       0  5012.1   0.035       0  5016.1   0.035       0
  5085.8    0.07       0  5264.5   0.035       0  5284.4    0.07       0
Bank Sta=5012.1,5016.1
Exp/Cntr=0.3,0.1

Type RM Length L Ch R = 1,1765,103,103,103
BEGIN DESCRIPTION:
Elm 01 48 3.0
END DESCRIPTION:
XS GIS Cut Line= 3
      1552980.45      6864055.60      1552395.42      6863954.91
      1551939.55      6863964.43
#Sta/Elev= 30
  4366.3 1775.47  4369.6 1775.41  4379.3 1775.30  4384.3 1774.15  4432.7 1773.90
  4444.3 1772.74  4483.4 1772.66  4504.2 1771.62  4554.0 1772.70  4559.0 1771.29
  4570.7 1771.32  4613.9 1772.09  4619.0 1770.79  4625.5 1770.71  4673.8 1771.97
  4678.9 1769.97  4733.7 1771.04  4738.8 1769.37  4793.6 1769.90  4798.7 1768.22
  4838.6 1769.11  4851.6 1768.21  4851.8 1767.71  4855.6 1768.21  5080.4 1773.34
  5100.4 1772.70  5140.4 1773.99  5267.7 1775.12  5370.4 1776.86  5415.9 1776.61
#Mann=6,-1,0
  4366.3   0.035       0  4369.6    0.07       0  4570.7   0.035       0
  4851.6   0.035       0  4855.6   0.035       0  5267.7    0.07       0
Bank Sta=4851.6,4855.6
Exp/Cntr=0.3,0.1

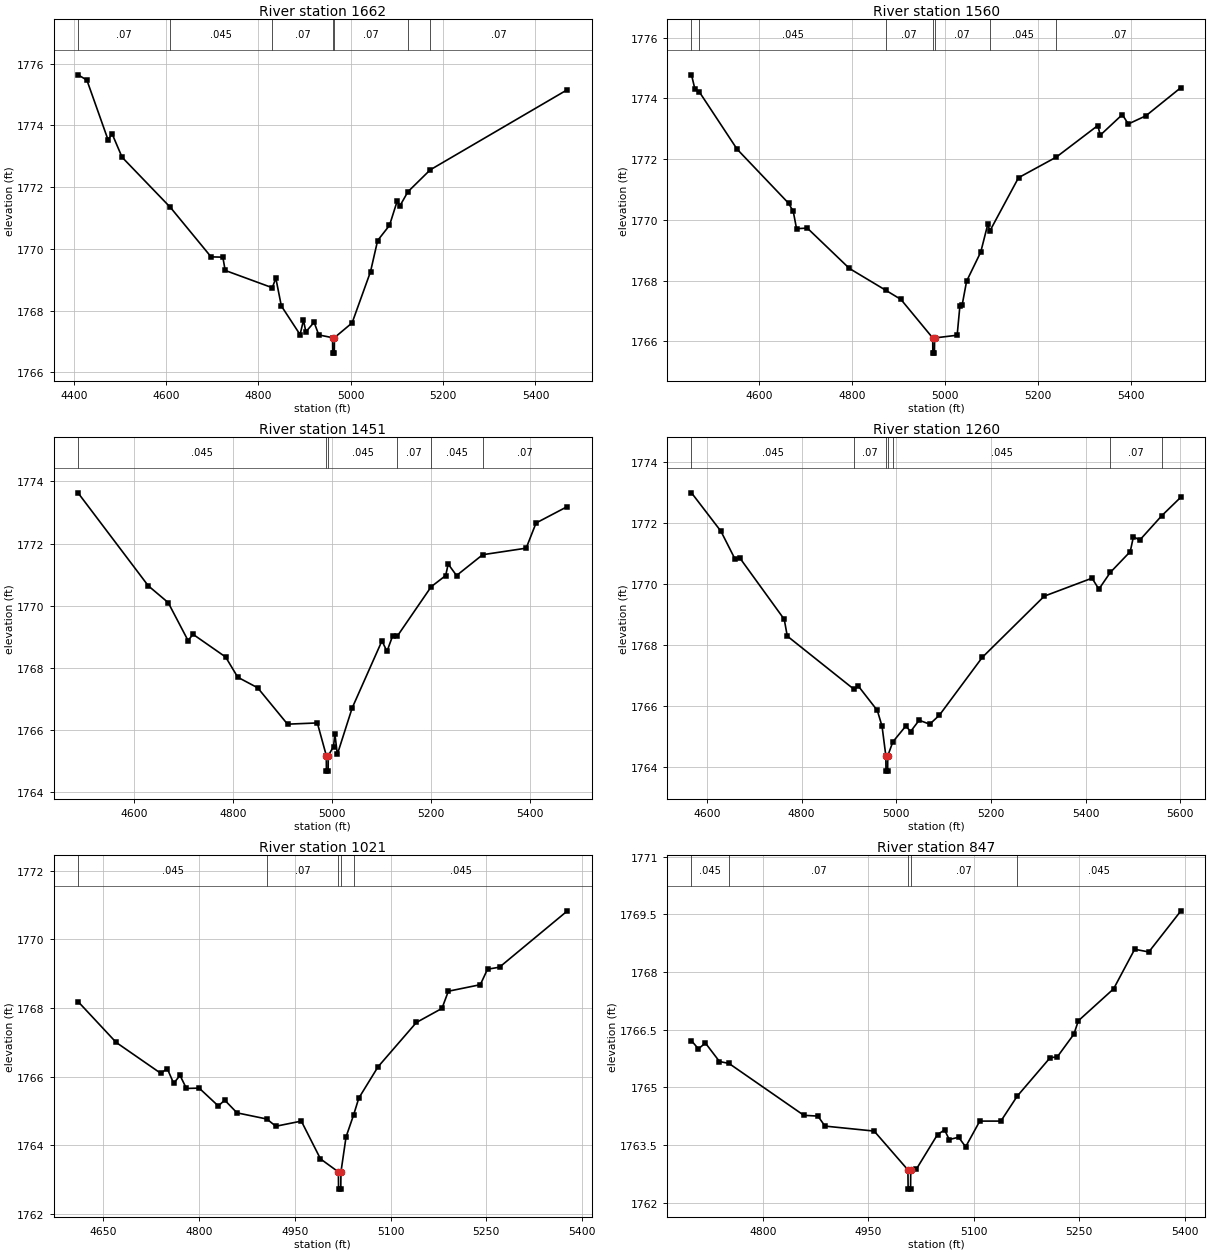
Type RM Length L Ch R = 1,1662,102,102,102
BEGIN DESCRIPTION:
Elm 01 48 1661.96
END DESCRIPTION:
XS GIS Cut Line= 3
      1552998.98      6863976.25      1552413.87      6863875.55
      1551959.54      6863769.77
#Sta/Elev= 30
  4409.1 1775.64  4428.3 1775.47  4474.0 1773.54  4483.2 1773.72  4504.5 1772.97
  4609.4 1771.34  4697.3 1769.74  4722.8 1769.73  4727.9 1769.30  4829.9 1768.74
  4837.6 1769.05  4849.5 1768.15  4890.1 1767.22  4897.5 1767.69  4902.6 1767.31
  4920.5 1767.62  4930.6 1767.21  4960.5 1767.12  4960.8 1766.62  4964.3 1766.62
  4964.5 1767.12  5002.8 1767.60  5042.7 1769.26  5058.1 1770.27  5083.8 1770.76
  5100.7 1771.56  5105.9 1771.38  5123.7 1771.85  5172.0 1772.56  5469.3 1775.16
#Mann=7,-1,0
  4409.1    0.07       0  4609.4   0.045       0  4829.9    0.07       0
  4960.5    0.07       0  4964.5    0.07       0  5123.7   0.045       0
  5172.0    0.07       0
Bank Sta=4960.5,4964.5
Exp/Cntr=0.3,0.1

Type RM Length L Ch R = 1,1560,109,109,109
BEGIN DESCRIPTION:
Elm 01 48 1560.34
END DESCRIPTION:
XS GIS Cut Line= 3
      1553002.41      6863847.77      1552462.48      6863788.74
      1551960.78      6863703.68
#Sta/Elev= 30
  4455.0 1774.78  4462.5 1774.30  4471.7 1774.22  4553.0 1772.33  4663.6 1770.55
  4673.7 1770.28  4680.8 1769.71  4703.9 1769.73  4794.4 1768.40  4872.7 1767.68
  4905.1 1767.38  4973.5 1766.11  4973.7 1765.61  4977.2 1765.61  4977.5 1766.11
  5026.0 1766.20  5031.8 1767.15  5036.9 1767.21  5046.3 1767.98  5076.7 1768.94
  5092.1 1769.87  5096.1 1769.63  5157.9 1771.39  5239.2 1772.07  5328.4 1773.11
  5333.5 1772.79  5381.0 1773.47  5393.8 1773.16  5431.7 1773.43  5507.0 1774.36
#Mann=7,-1,0
  4455.0    0.07       0  4471.7   0.045       0  4872.7    0.07       0
  4973.5    0.07       0  4977.5    0.07       0  5096.1   0.045       0
  5239.2    0.07       0
Bank Sta=4973.5,4977.5
Exp/Cntr=0.3,0.1

Type RM Length L Ch R = 1,1451,191,191,191
BEGIN DESCRIPTION:
Elm 01 48 1450.83
END DESCRIPTION:
XS GIS Cut Line= 3
      1553016.31      6863740.13      1552502.41      6863693.26
      1552031.89      6863651.59
#Sta/Elev= 30
  4486.6 1773.63  4628.5 1770.64  4668.7 1770.10  4708.8 1768.88  4718.9 1769.08
  4784.7 1768.35  4809.2 1767.70  4849.4 1767.36  4909.7 1766.19  4969.9 1766.23
  4988.0 1765.18  4988.2 1764.68  4991.7 1764.68  4992.0 1765.18  5002.6 1765.47
  5005.3 1765.88  5010.3 1765.22  5040.2 1766.71  5100.4 1768.87  5110.5 1768.53
  5122.2 1769.04  5130.9 1769.01  5199.8 1770.61  5229.1 1770.97  5234.1 1771.34
  5251.0 1770.97  5303.8 1771.64  5391.6 1771.85  5411.6 1772.66  5475.0 1773.19
#Mann=6,-1,0
  4486.6   0.045       0  4988.0   0.045       0  4992.0   0.045       0
  5130.9    0.07       0  5199.8   0.045       0  5303.8    0.07       0
Bank Sta=4988,4992
Exp/Cntr=0.3,0.1

Type RM Length L Ch R = 1,1260,239,239,239
BEGIN DESCRIPTION:
Elm 01 48 1259.78
END DESCRIPTION:
XS GIS Cut Line= 3
      1553037.09      6863583.88      1552603.10      6863559.58
      1552008.79      6863479.87
#Sta/Elev= 30
  4567.2 1772.99  4629.4 1771.73  4659.4 1770.81  4669.5 1770.85  4763.2 1768.84
  4769.6 1768.29  4911.0 1766.54  4919.8 1766.65  4959.9 1765.85  4969.9 1765.33
  4977.9 1764.36  4978.2 1763.86  4981.7 1763.86  4981.9 1764.36  4992.7 1764.82
  5020.1 1765.34  5030.2 1765.16  5048.3 1765.53  5070.6 1765.40  5090.8 1765.69
  5181.6 1767.59  5312.7 1769.60  5413.6 1770.19  5428.1 1769.83  5452.3 1770.38
  5494.3 1771.06  5501.1 1771.55  5514.5 1771.44  5561.0 1772.24  5601.5 1772.85
#Mann=7,-1,0
  4567.2   0.045       0  4911.0    0.07       0  4977.9   0.045       0
  4981.9    0.07       0  4992.7   0.045       0  5452.3    0.07       0
  5561.0   0.045       0
Bank Sta=4977.9,4981.9
Exp/Cntr=0.3,0.1

Type RM Length L Ch R = 1,1021,174,174,174
BEGIN DESCRIPTION:
Elm 01 48 1020.84
END DESCRIPTION:
XS GIS Cut Line= 3
      1552894.74      6863392.91      1552495.46      6863377.28
      1552128.74      6863401.50
#Sta/Elev= 30
  4610.2 1768.19  4670.0 1767.00  4740.0 1766.10  4750.0 1766.24  4760.1 1765.81
  4770.1 1766.04  4780.1 1765.66  4800.1 1765.67  4830.1 1765.15  4840.1 1765.32
  4859.4 1764.95  4906.2 1764.77  4920.2 1764.56  4960.2 1764.71  4990.2 1763.61
  5018.3 1763.23  5018.5 1762.73  5022.0 1762.73  5022.3 1763.23  5030.3 1764.25
  5042.3 1764.90  5050.3 1765.38  5080.4 1766.29  5140.5 1767.58  5180.6 1767.99
  5190.6 1768.49  5240.7 1768.68  5252.0 1769.13  5270.8 1769.19  5377.3 1770.83
#Mann=5,-1,0
  4610.2   0.045       0  4906.2    0.07       0  5018.3    0.07       0
  5022.3    0.07       0  5042.3   0.045       0
Bank Sta=5018.3,5022.3
Exp/Cntr=0.3,0.1

Type RM Length L Ch R = 1,847,226,226,226
BEGIN DESCRIPTION:
Elm 01 48 846.95
END DESCRIPTION:
XS GIS Cut Line= 3
      1552854.79      6863221.03      1552551.02      6863219.30
      1552159.34      6863241.83
#Sta/Elev= 30
  4698.6 1766.21  4708.4 1766.00  4718.4 1766.15  4738.4 1765.67  4751.9 1765.62
  4858.4 1764.27  4878.4 1764.25  4888.4 1763.99  4958.4 1763.86  5006.4 1762.85
  5006.7 1762.35  5010.2 1762.35  5010.4 1762.85  5018.4 1762.87  5048.5 1763.77
  5058.5 1763.89  5065.2 1763.64  5078.5 1763.70  5088.5 1763.45  5108.6 1764.12
  5138.6 1764.12  5161.9 1764.77  5208.7 1765.77  5218.8 1765.79  5242.4 1766.38
  5248.8 1766.73  5298.9 1767.56  5328.9 1768.59  5349.0 1768.52  5394.7 1769.59
#Mann=5,-1,0
  4698.6   0.045       0  4751.9    0.07       0  5006.4    0.07       0
  5010.4    0.07       0  5161.9   0.045       0
Bank Sta=5006.4,5010.4
Exp/Cntr=0.3,0.1

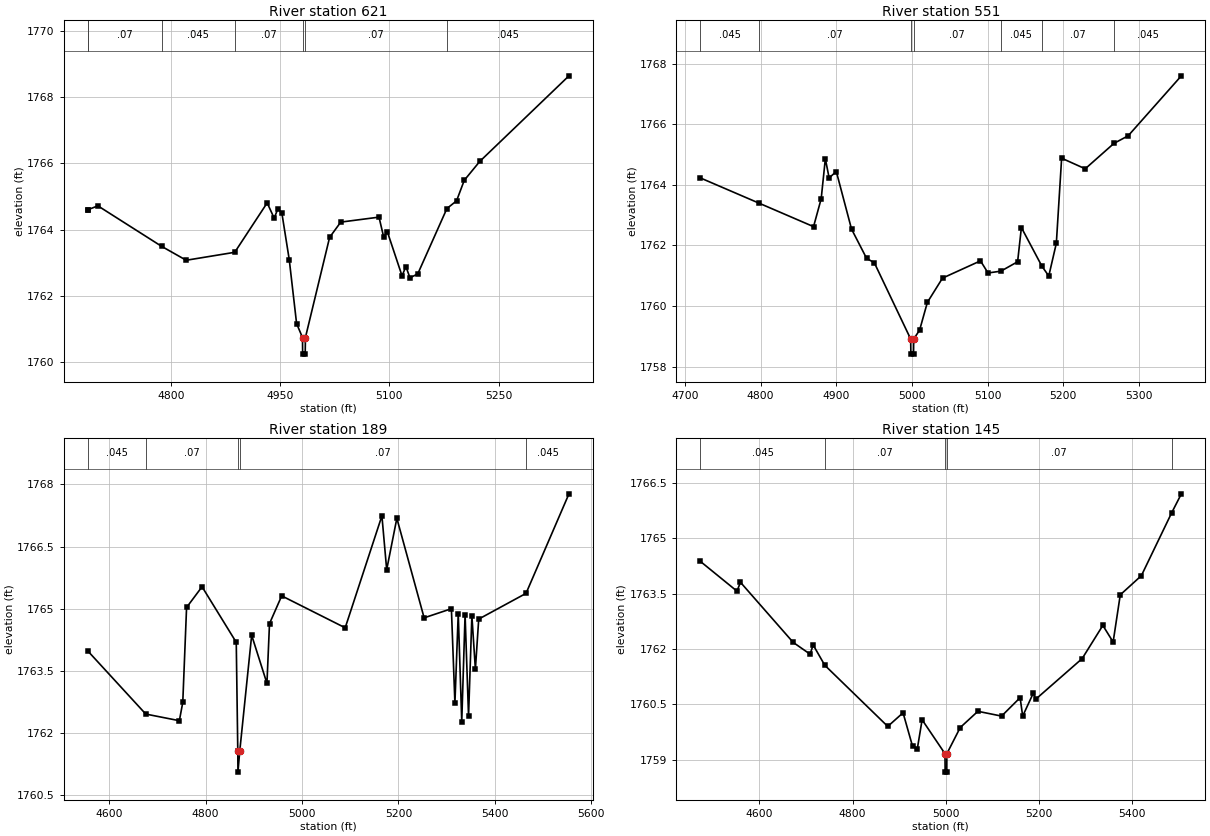
Type RM Length L Ch R = 1,621,70,70,70
BEGIN DESCRIPTION:
Elm 01 48 679.31
END DESCRIPTION:
XS GIS Cut Line= 3
      1552808.66      6862996.54      1552452.76      6863046.88
      1552169.87      6863149.28
#Sta/Elev= 30
  4686.1 1764.61  4686.9 1764.61  4699.9 1764.72  4787.3 1763.50  4821.1 1763.08
  4887.7 1763.32  4932.2 1764.81  4941.8 1764.35  4946.9 1764.63  4952.4 1764.50
  4962.5 1763.10  4972.6 1761.17  4980.7 1760.75  4980.9 1760.25  4984.4 1760.25
  4984.7 1760.75  5017.9 1763.77  5033.2 1764.23  5085.7 1764.38  5092.0 1763.79
  5097.3 1763.93  5117.3 1762.61  5122.6 1762.89  5128.2 1762.55  5138.9 1762.67
  5178.9 1764.64  5192.1 1764.87  5202.7 1765.49  5224.0 1766.06  5346.4 1768.64
#Mann=7,-1,0
  4686.1   0.045       0  4686.9    0.07       0  4787.3   0.045       0
  4887.7    0.07       0  4980.7    0.07       0  4984.7    0.07       0
  5178.9   0.045       0
Bank Sta=4980.7,4984.7
Exp/Cntr=0.3,0.1

Type RM Length L Ch R = 1,551,362,362,362
BEGIN DESCRIPTION:
Elm 01 48 546.15
END DESCRIPTION:
XS GIS Cut Line= 3
      1552784.37      6862950.13      1552305.96      6862987.36
      1552201.20      6863103.28
#Sta/Elev= 30
  4720.2 1764.23  4798.4 1763.39  4870.0 1762.62  4880.1 1763.54  4885.6 1764.86
  4890.6 1764.23  4900.1 1764.44  4920.2 1762.54  4940.2 1761.57  4950.3 1761.43
  4998.4 1758.91  4998.7 1758.41  5002.2 1758.41  5002.4 1758.91  5010.2 1759.20
  5020.5 1760.12  5040.5 1760.92  5090.7 1761.49  5100.7 1761.09  5117.7 1761.15
  5139.8 1761.46  5144.8 1762.59  5172.0 1761.31  5181.0 1760.99  5191.0 1762.07
  5198.0 1764.88  5229.2 1764.53  5267.2 1765.37  5286.0 1765.62  5356.3 1767.60
#Mann=7,-1,0
  4720.2   0.045       0  4798.4    0.07       0  4998.4    0.07       0
  5002.4    0.07       0  5117.7   0.045       0  5172.0    0.07       0
  5267.2   0.045       0
Bank Sta=4998.4,5002.4
Exp/Cntr=0.3,0.1

Type RM Length L Ch R = 1,189,44,44,44
BEGIN DESCRIPTION:
Elm 01 48 191.04
END DESCRIPTION:
XS GIS Cut Line= 6
      1552779.07      6862897.47      1552598.97      6862777.72
      1552558.27      6862651.61      1552505.33      6862633.37
      1552455.53      6862818.26      1552189.95      6863097.73
#Sta/Elev= 30
  4555.5 1763.98  4675.7 1762.46  4745.4 1762.30  4752.5 1762.74  4760.4 1765.03
  4792.5 1765.53  4863.5 1764.19  4866.7 1761.56  4867.0 1761.06  4870.7 1761.56
  4895.5 1764.36  4927.2 1763.20  4932.5 1764.64  4957.8 1765.31  5089.6 1764.54
  5165.8 1767.24  5175.7 1765.94  5196.8 1767.18  5253.4 1764.78  5310.0 1765.00
  5317.3 1762.72  5324.2 1764.88  5331.5 1762.28  5338.4 1764.86  5345.6 1762.41
  5352.5 1764.83  5359.8 1763.54  5366.7 1764.75  5464.9 1765.37  5554.0 1767.77
#Mann=5,-1,0
  4555.5   0.045       0  4675.7    0.07       0  4866.7    0.07       0
  4870.7    0.07       0  5464.9   0.045       0
Bank Sta=4866.7,4870.7
Exp/Cntr=0.3,0.1

Type RM Length L Ch R = 1,145,0,0,0
BEGIN DESCRIPTION:
Elm 01 48 69.678
END DESCRIPTION:
XS GIS Cut Line= 4
      1552836.39      6862898.11      1552574.65      6862589.22
      1552412.41      6862623.75      1552212.68      6863039.96
#Sta/Elev= 30
  4473.2 1764.38  4552.0 1763.57  4559.5 1763.81  4672.6 1762.18  4708.9 1761.86
  4715.5 1762.11  4740.4 1761.56  4875.6 1759.90  4908.4 1760.27  4928.8 1759.36
  4939.1 1759.30  4949.3 1760.08  4998.4 1759.16  4998.7 1758.66  5002.2 1758.66
  5002.4 1759.16  5031.1 1759.87  5069.0 1760.31  5119.8 1760.18  5159.6 1760.68
  5165.1 1760.18  5187.8 1760.80  5193.3 1760.64  5292.7 1761.74  5337.1 1762.64
  5359.2 1762.19  5374.5 1763.47  5419.8 1763.99  5484.6 1765.69  5505.6 1766.21
#Mann=5,-1,0
  4473.2   0.045       0  4740.4    0.07       0  4998.4    0.07       0
  5002.4    0.07       0  5484.6   0.045       0
Bank Sta=4998.4,5002.4
Exp/Cntr=0.3,0.1

Chan Stop Cuts=-1