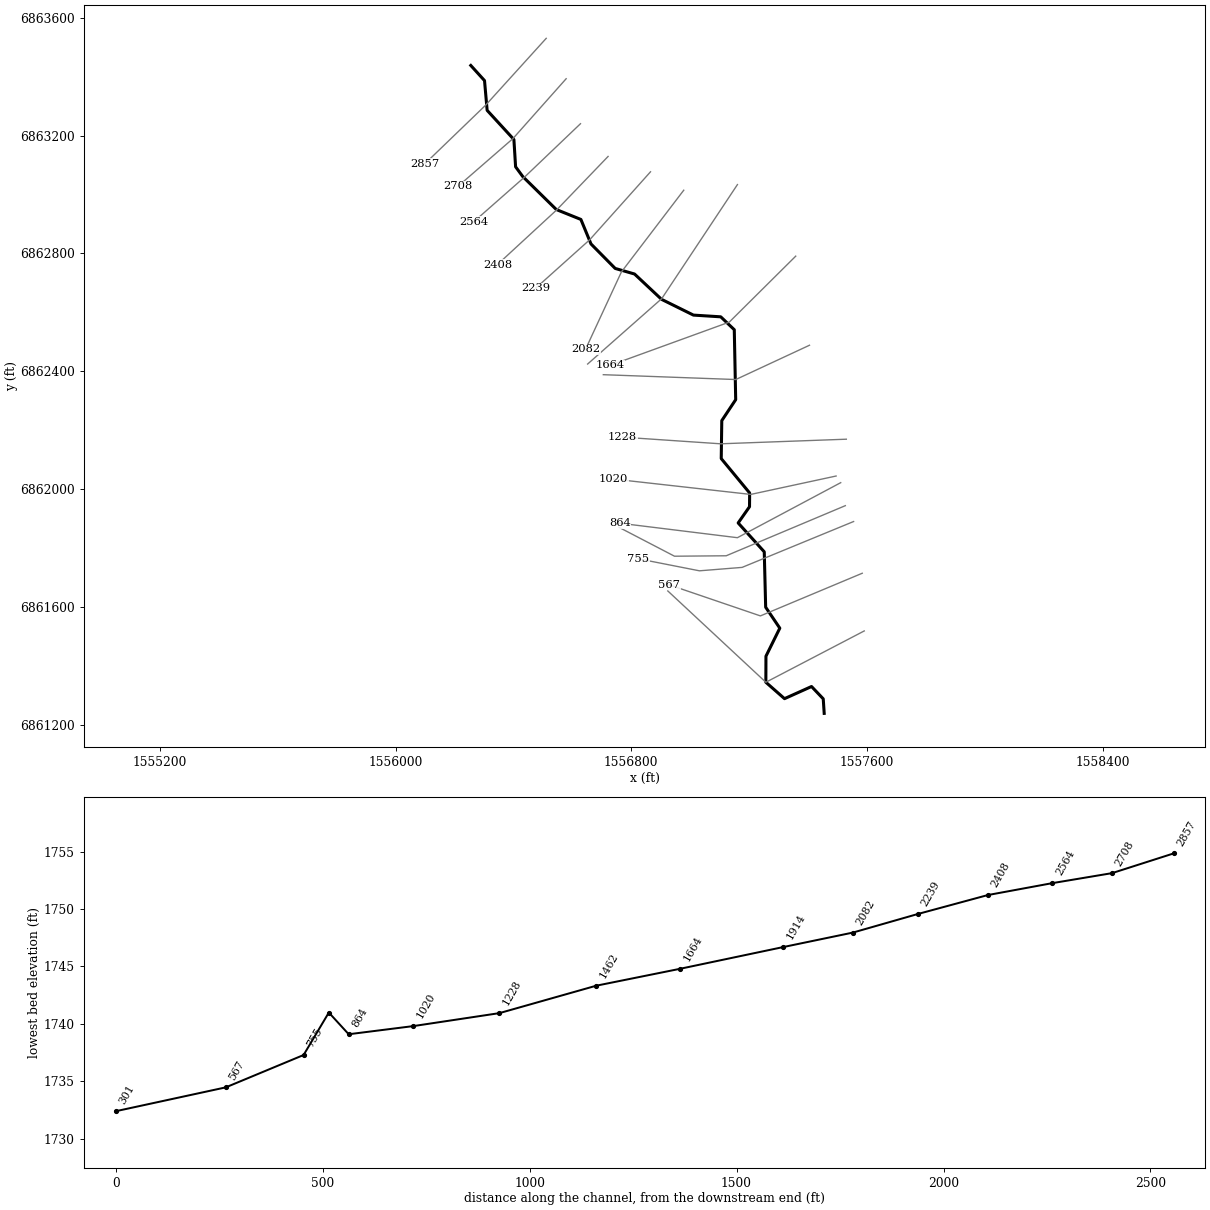
--- Elm 01 49.prj (project) ---

Proj Title=Elm 01 49 Base Level Engineering
Current Plan=p01
Default Exp/Contr=0.3,0.1
English Units
Geom File=g01
Flow File=f01
Plan File=p01
BEGIN DESCRIPTION:
Elm 01 49
END DESCRIPTION:

--- Elm 01 49.p01 (plan) ---

Plan Title=Multiple Run
Short Identifier=Multiple
Geom File=g01
Flow File=f01
Subcritical Flow
K Sum by GR= 0
Std Step Tol= 0.01
Critical Tol= 0.01
Num of Std Step Trials= 20
Max Error Tol= 0.3
Flow Tol Ratio= 0.001
Split Flow NTrial= 30
Split Flow Tol= 0.02
Split Flow Ratio= 0.02
Log Output Level= 0
Friction Slope Method= 1
Unsteady Friction Slope Method= 2
Unsteady Bridges Friction Slope Method= 1
Parabolic Critical Depth
Global Vel Dist=  1 , 1 , 1
Global Log Level= 0
CheckData=True
Encroach Param= -1, 0, 0, 0
BEGIN DESCRIPTION:
Multiple Run
END DESCRIPTION:

--- Elm 01 49.f01 (steady flow) ---

Flow Title=Multiple
Number of Profiles=7
Profile Names=10-year,25-year,50-year,1pct_min,100-year,1pct_plu,500-year
River Rch & RM= Elm 01 49,Reach-1,2857
      73      93     108      79     126     174     173
Boundary for River Rch & Prof#=Elm 01 49,Reach-1,1
Up Type=0
Dn Type=3
Dn Slope=0.005
Boundary for River Rch & Prof#=Elm 01 49,Reach-1,2
Up Type=0
Dn Type=3
Dn Slope=0.005
Boundary for River Rch & Prof#=Elm 01 49,Reach-1,3
Up Type=0
Dn Type=3
Dn Slope=0.005
Boundary for River Rch & Prof#=Elm 01 49,Reach-1,4
Up Type=0
Dn Type=3
Dn Slope=0.005
Boundary for River Rch & Prof#=Elm 01 49,Reach-1,5
Up Type=0
Dn Type=3
Dn Slope=0.005
Boundary for River Rch & Prof#=Elm 01 49,Reach-1,6
Up Type=0
Dn Type=3
Dn Slope=0.005
Boundary for River Rch & Prof#=Elm 01 49,Reach-1,7
Up Type=0
Dn Type=3
Dn Slope=0.005

--- Elm 01 49.g01 (geometry) ---

Geom Title=Existing Conditions

River Reach=Elm 01 49,Reach-1
Reach XY= 30
      1556255.00      6863438.00      1556301.61      6863386.59
      1556310.52      6863285.57      1556401.37      6863186.50
      1556407.15      6863093.89      1556431.18      6863061.13
      1556545.34      6862948.79      1556628.84      6862915.14
      1556663.16      6862831.95      1556745.30      6862748.77
      1556811.04      6862729.82      1556902.71      6862643.84
      1557010.97      6862590.34      1557103.75      6862584.49
      1557149.66      6862540.74      1557154.48      6862303.22
      1557107.25      6862232.06      1557105.37      6862103.17
      1557201.83      6861986.35      1557201.41      6861939.65
      1557162.84      6861884.60      1557251.44      6861786.54
      1557256.24      6861598.50      1557304.23      6861527.31
      1557257.19      6861432.03      1557256.89      6861343.66
      1557320.22      6861287.95      1557411.96      6861329.19
      1557451.73      6861287.37      1557455.00      6861238.00

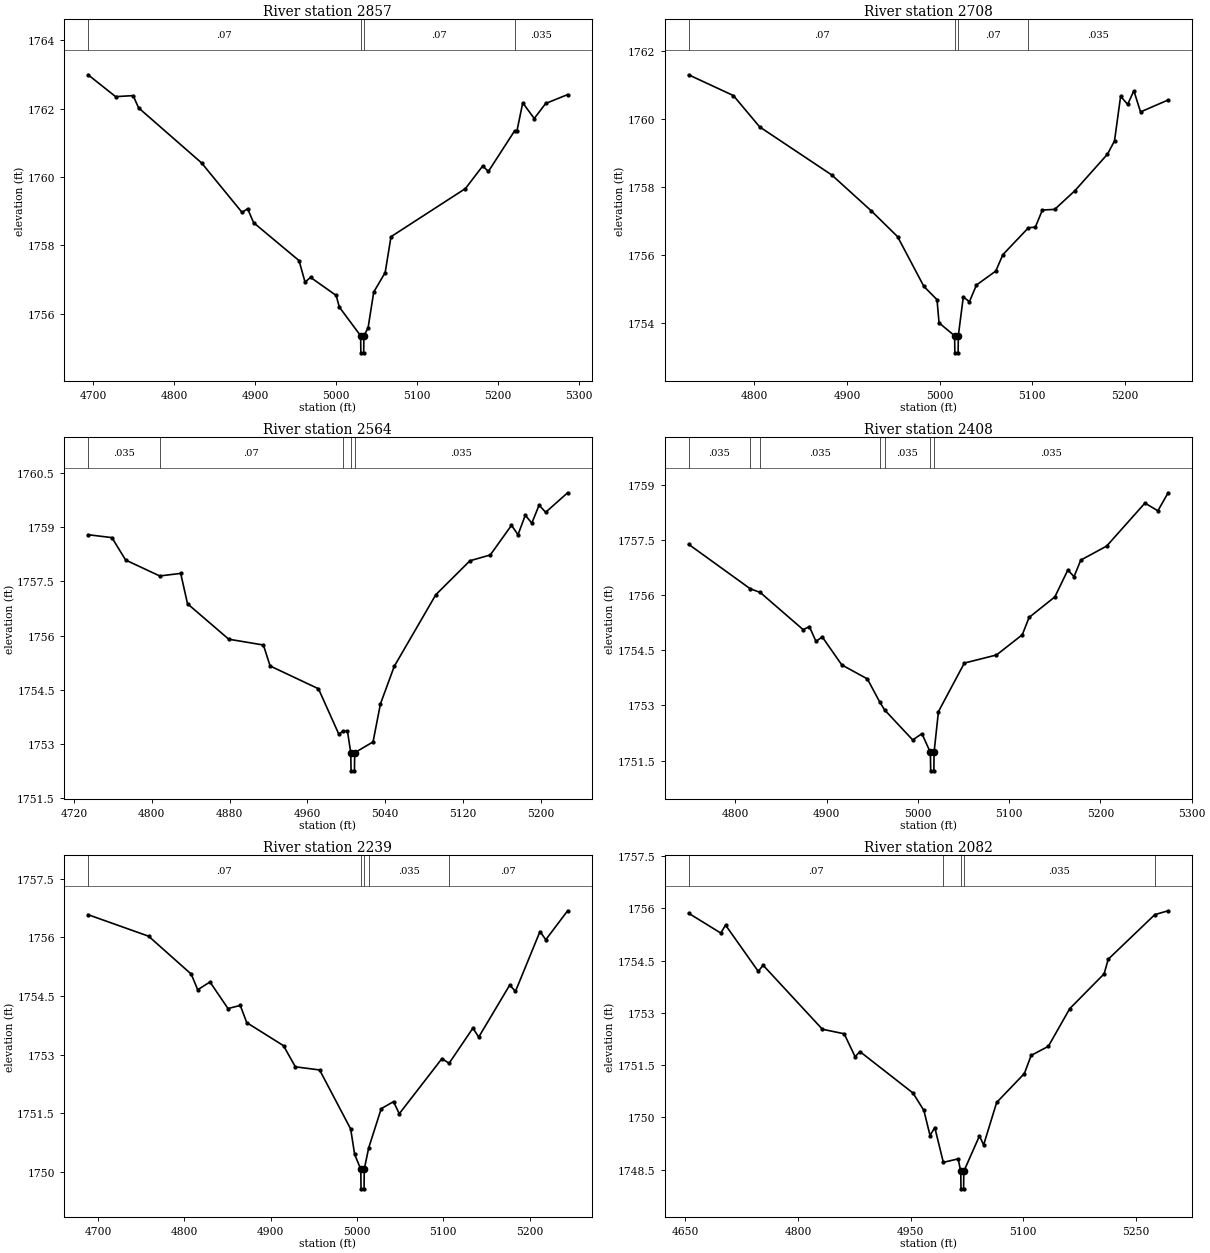
Type RM Length L Ch R = 1,2857,149,149,149
BEGIN DESCRIPTION:
Elm 01 49 2856.7
END DESCRIPTION:
XS GIS Cut Line= 3
      1556511.10      6863530.08      1556305.48      6863303.20
      1556099.81      6863104.89
#Sta/Elev= 30
  4693.8 1762.99  4727.8 1762.35  4749.4 1762.38  4756.2 1762.02  4833.9 1760.41
  4883.9 1758.96  4890.7 1759.07  4898.1 1758.66  4954.2 1757.55  4961.6 1756.92
  4968.4 1757.06  5000.0 1756.53  5003.9 1756.19  5030.2 1755.35  5030.5 1754.85
  5034.0 1754.85  5034.2 1755.35  5039.4 1755.58  5046.4 1756.63  5060.5 1757.20
  5067.7 1758.25  5159.6 1759.66  5180.9 1760.32  5187.9 1760.16  5220.3 1761.35
  5223.1 1761.34  5230.3 1762.17  5244.5 1761.71  5258.6 1762.15  5285.7 1762.41
#Mann=4,-1,0
  4693.8    0.07       0  5030.2    0.07       0  5034.2    0.07       0
  5220.3   0.035       0
Bank Sta=5030.2,5034.2
Exp/Cntr=0.3,0.1

Type RM Length L Ch R = 1,2708,144,144,144
BEGIN DESCRIPTION:
Elm 01 49 2708.24
END DESCRIPTION:
XS GIS Cut Line= 3
      1556578.80      6863392.92      1556398.24      6863189.78
      1556212.48      6863028.33
#Sta/Elev= 30
  4728.9 1761.29  4777.3 1760.68  4805.7 1759.76  4883.5 1758.35  4926.1 1757.30
  4954.6 1756.54  4983.0 1755.08  4997.2 1754.69  4999.4 1754.01  5016.2 1753.63
  5016.5 1753.13  5020.0 1753.13  5020.2 1753.63  5025.6 1754.77  5032.2 1754.63
  5039.8 1755.12  5060.7 1755.53  5068.3 1756.01  5095.9 1756.80  5103.4 1756.82
  5111.0 1757.32  5124.3 1757.34  5146.2 1757.89  5181.3 1758.96  5188.9 1759.35
  5195.5 1760.66  5203.1 1760.42  5209.8 1760.82  5217.0 1760.20  5246.8 1760.55
#Mann=4,-1,0
  4728.9    0.07       0  5016.2    0.07       0  5020.2    0.07       0
  5095.9   0.035       0
Bank Sta=5016.2,5020.2
Exp/Cntr=0.3,0.1

Type RM Length L Ch R = 1,2564,156,156,156
BEGIN DESCRIPTION:
Elm 01 49 2563.84
END DESCRIPTION:
XS GIS Cut Line= 3
      1556627.44      6863240.16      1556438.17      6863059.58
      1556264.53      6862906.77
#Sta/Elev= 30
  4734.6 1758.79  4759.1 1758.71  4773.2 1758.09  4808.2 1757.65  4829.8 1757.72
  4836.8 1756.88  4879.2 1755.90  4914.8 1755.74  4921.7 1755.16  4971.4 1754.53
  4992.4 1753.27  4996.5 1753.36  5001.2 1753.36  5004.6 1752.76  5004.9 1752.26
  5008.4 1752.26  5008.6 1752.76  5027.5 1753.06  5035.1 1754.11  5049.3 1755.15
  5092.0 1757.13  5127.1 1758.07  5148.0 1758.23  5169.8 1759.05  5176.5 1758.79
  5184.0 1759.33  5190.7 1759.11  5198.2 1759.61  5204.9 1759.41  5227.5 1759.95
#Mann=5,-1,0
  4734.6   0.035       0  4808.2    0.07       0  4996.5   0.035       0
  5004.6   0.035       0  5008.6   0.035       0
Bank Sta=5004.6,5008.6
Exp/Cntr=0.3,0.1

Type RM Length L Ch R = 1,2408,169,169,169
BEGIN DESCRIPTION:
Elm 01 49 2407.64
END DESCRIPTION:
XS GIS Cut Line= 3
      1556721.18      6863129.04      1556545.81      6862946.73
      1556345.49      6862761.95
#Sta/Elev= 30
  4748.7 1757.38  4816.3 1756.17  4827.2 1756.07  4874.2 1755.06  4881.1 1755.14
  4888.3 1754.74  4895.2 1754.86  4916.6 1754.10  4944.6 1753.72  4958.2 1753.09
  4963.4 1752.88  4994.3 1752.06  5004.4 1752.23  5013.7 1751.72  5014.0 1751.22
  5017.5 1751.22  5017.7 1751.72  5022.5 1752.83  5050.9 1754.15  5086.1 1754.37
  5114.4 1754.92  5121.8 1755.39  5150.1 1755.95  5164.3 1756.68  5171.1 1756.50
  5178.5 1756.95  5206.8 1757.33  5248.8 1758.50  5263.0 1758.29  5274.2 1758.78
#Mann=7,-1,0
  4748.7   0.035       0  4816.3    0.07       0  4827.2   0.035       0
  4958.2    0.07       0  4963.4   0.035       0  5013.7   0.035       0
  5017.7   0.035       0
Bank Sta=5013.7,5017.7
Exp/Cntr=0.3,0.1

Type RM Length L Ch R = 1,2239,157,157,157
BEGIN DESCRIPTION:
Elm 01 49 2238.79
END DESCRIPTION:
XS GIS Cut Line= 3
      1556865.25      6863076.94      1556658.66      6862846.03
      1556475.71      6862682.07
#Sta/Elev= 30
  4688.5 1756.58  4758.6 1756.03  4808.0 1755.06  4815.5 1754.66  4829.7 1754.86
  4850.6 1754.18  4864.8 1754.26  4872.3 1753.82  4914.9 1753.23  4928.6 1752.69
  4956.7 1752.61  4992.7 1751.10  4997.3 1750.45  5004.4 1750.07  5004.7 1749.57
  5008.2 1749.57  5008.4 1750.07  5013.6 1750.62  5028.1 1751.62  5042.3 1751.80
  5049.0 1751.49  5098.4 1752.90  5106.7 1752.78  5134.3 1753.68  5141.0 1753.45
  5176.9 1754.78  5183.6 1754.62  5212.0 1756.15  5218.7 1755.94  5244.0 1756.68
#Mann=5,-1,0
  4688.5    0.07       0  5004.4    0.07       0  5008.4    0.07       0
  5013.6   0.035       0  5106.7    0.07       0
Bank Sta=5004.4,5008.4
Exp/Cntr=0.3,0.1

Type RM Length L Ch R = 1,2082,168,168,168
BEGIN DESCRIPTION:
Elm 01 49 2082.35
END DESCRIPTION:
XS GIS Cut Line= 3
      1556978.10      6863014.43      1556766.30      6862736.66
      1556644.75      6862474.47
#Sta/Elev= 30
  4654.4 1755.86  4697.3 1755.29  4703.6 1755.52  4747.2 1754.19  4753.5 1754.37
  4832.5 1752.53  4861.5 1752.40  4876.1 1751.74  4882.4 1751.89  4953.1 1750.70
  4967.6 1750.20  4975.8 1749.48  4982.1 1749.71  4993.5 1748.71  5013.2 1748.81
  5016.7 1748.45  5017.0 1747.95  5020.5 1747.95  5020.7 1748.45  5041.6 1749.47
  5047.1 1749.21  5064.5 1750.43  5101.4 1751.26  5110.4 1751.78  5133.3 1752.04
  5161.7 1753.12  5207.5 1754.12  5213.0 1754.54  5275.0 1755.82  5292.7 1755.93
#Mann=5,-1,0
  4654.4    0.07       0  4993.5   0.035       0  5016.7   0.035       0
  5020.7   0.035       0  5275.0    0.07       0
Bank Sta=5016.7,5020.7
Exp/Cntr=0.3,0.1

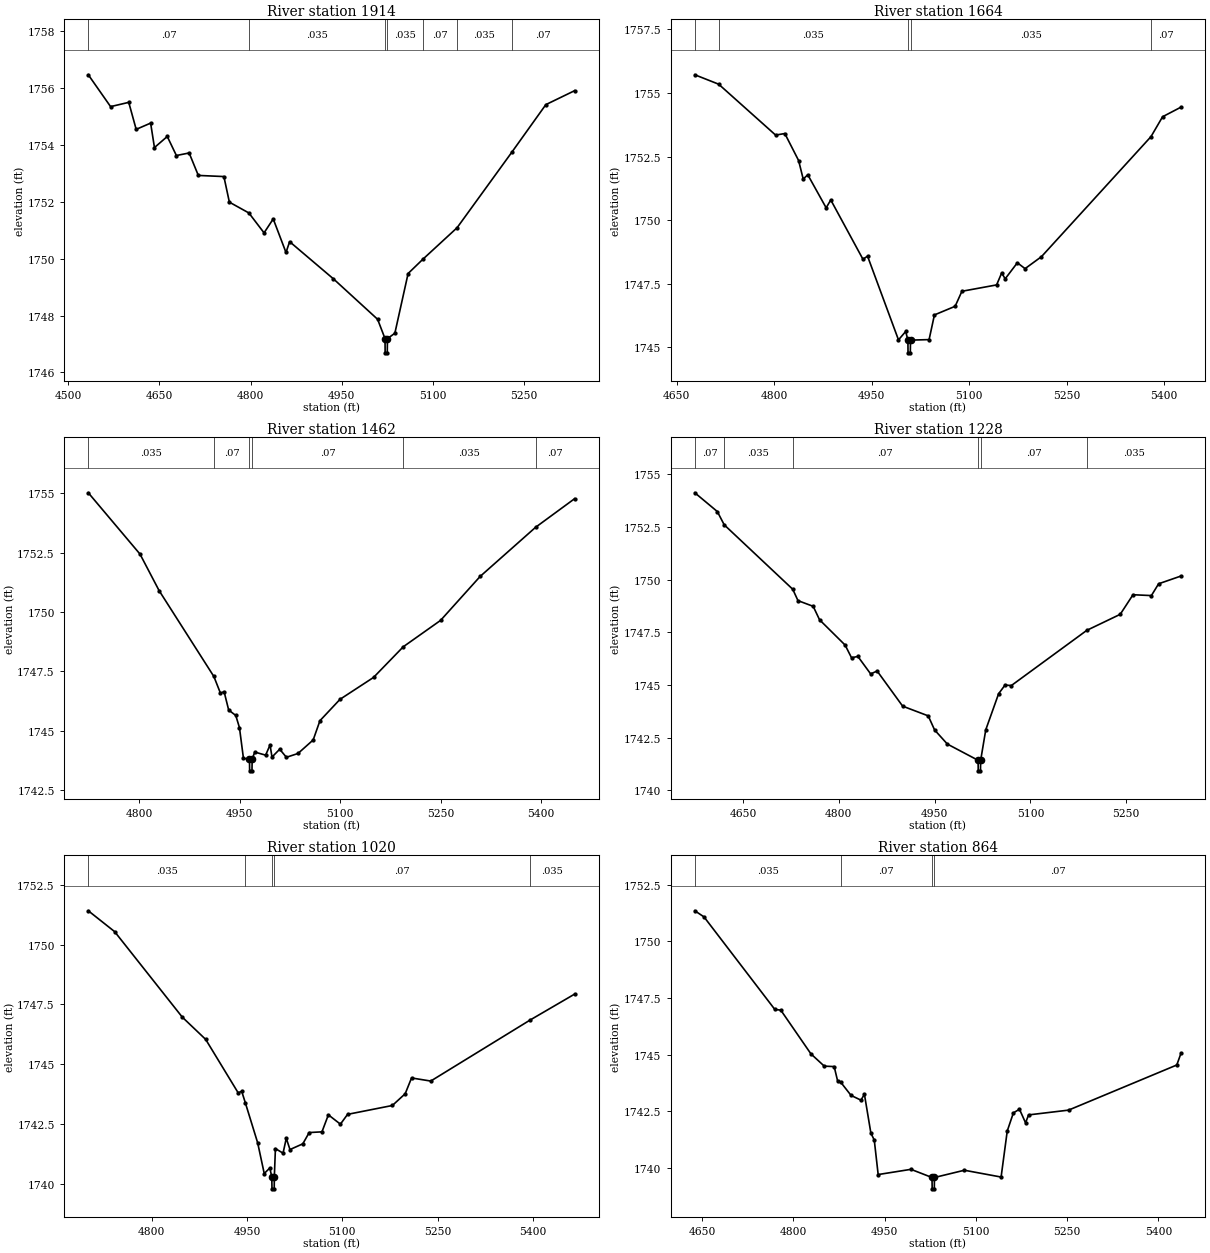
Type RM Length L Ch R = 1,1914,250,250,250
BEGIN DESCRIPTION:
Elm 01 49 1914.13
END DESCRIPTION:
XS GIS Cut Line= 3
      1557160.38      6863033.51      1556903.45      6862646.38
      1556651.73      6862424.17
#Sta/Elev= 30
  4533.0 1756.47  4569.7 1755.35  4599.6 1755.50  4611.8 1754.55  4635.6 1754.77
  4641.9 1753.91  4663.0 1754.30  4678.0 1753.63  4699.0 1753.72  4714.1 1752.93
  4756.2 1752.89  4765.2 1751.99  4797.3 1751.61  4822.3 1750.91  4837.4 1751.40
  4858.4 1750.22  4864.4 1750.60  4936.6 1749.29  5009.2 1747.87  5021.4 1747.19
  5021.6 1746.69  5025.1 1746.69  5025.4 1747.19  5037.6 1747.38  5059.4 1749.48
  5083.6 1749.98  5140.0 1751.09  5229.9 1753.74  5286.1 1755.42  5333.4 1755.91
#Mann=7,-1,0
  4533.0    0.07       0  4797.3   0.035       0  5021.4   0.035       0
  5025.4   0.035       0  5083.6    0.07       0  5140.0   0.035       0
  5229.9    0.07       0
Bank Sta=5021.4,5025.4
Exp/Cntr=0.3,0.1

Type RM Length L Ch R = 1,1664,202,202,202
BEGIN DESCRIPTION:
Elm 01 49 1663.87
END DESCRIPTION:
XS GIS Cut Line= 3
      1557358.34      6862790.50      1557132.62      6862566.52
      1556728.17      6862419.60
#Sta/Elev= 30
  4677.8 1755.72  4714.5 1755.35  4802.1 1753.35  4816.3 1753.41  4837.5 1752.35
  4844.6 1751.62  4851.6 1751.79  4879.9 1750.49  4887.0 1750.80  4936.5 1748.47
  4943.6 1748.59  4991.2 1745.30  5002.3 1745.63  5005.7 1745.29  5005.9 1744.79
  5009.4 1744.79  5009.7 1745.29  5038.3 1745.31  5046.5 1746.28  5078.4 1746.62
  5088.8 1747.21  5142.2 1747.46  5150.0 1747.93  5155.4 1747.70  5174.1 1748.33
  5186.0 1748.10  5211.2 1748.57  5379.8 1753.29  5397.6 1754.07  5426.1 1754.45
#Mann=5,-1,0
  4677.8    0.07       0  4714.5   0.035       0  5005.7   0.035       0
  5009.7   0.035       0  5379.8    0.07       0
Bank Sta=5005.7,5009.7
Exp/Cntr=0.3,0.1

Type RM Length L Ch R = 1,1462,234,234,234
BEGIN DESCRIPTION:
Elm 01 49 1461.777
END DESCRIPTION:
XS GIS Cut Line= 3
      1557405.04      6862488.02      1557154.81      6862371.56
      1556705.01      6862388.00
#Sta/Elev= 30
  4724.0 1755.02  4801.2 1752.44  4829.8 1750.90  4911.5 1747.29  4921.3 1746.59
  4926.8 1746.65  4933.6 1745.88  4944.2 1745.65  4949.7 1745.14  4955.7 1743.84
  4964.7 1743.82  4964.9 1743.32  4968.4 1743.32  4968.7 1743.82  4972.6 1744.11
  4988.8 1743.98  4995.4 1744.41  4998.3 1743.90  5009.8 1744.23  5019.8 1743.89
  5037.1 1744.05  5059.8 1744.62  5069.9 1745.43  5099.9 1746.33  5149.9 1747.25
  5194.3 1748.54  5250.0 1749.65  5309.1 1751.50  5392.0 1753.57  5450.1 1754.77
#Mann=6,-1,0
  4724.0   0.035       0  4911.5    0.07       0  4964.7    0.07       0
  4968.7    0.07       0  5194.3   0.035       0  5392.0    0.07       0
Bank Sta=4964.7,4968.7
Exp/Cntr=0.3,0.1

Type RM Length L Ch R = 1,1228,208,208,208
BEGIN DESCRIPTION:
Elm 01 49 1228
END DESCRIPTION:
XS GIS Cut Line= 3
      1557530.16      6862168.95      1557103.10      6862153.33
      1556769.91      6862175.89
#Sta/Elev= 30
  4574.5 1754.13  4609.7 1753.24  4620.5 1752.61  4727.8 1749.55  4736.0 1749.01
  4759.8 1748.74  4769.8 1748.10  4809.8 1746.90  4819.8 1746.30  4829.8 1746.36
  4849.8 1745.53  4859.9 1745.67  4899.9 1744.00  4939.9 1743.54  4949.9 1742.87
  4969.9 1742.20  5018.0 1741.43  5018.2 1740.93  5021.7 1740.93  5022.0 1741.43
  5030.0 1742.88  5050.1 1744.59  5060.1 1745.00  5070.1 1744.98  5188.2 1747.60
  5240.5 1748.36  5260.5 1749.29  5289.3 1749.25  5300.6 1749.81  5335.8 1750.18
#Mann=6,-1,0
  4574.5    0.07       0  4620.5   0.035       0  4727.8    0.07       0
  5018.0    0.07       0  5022.0    0.07       0  5188.2   0.035       0
Bank Sta=5018,5022
Exp/Cntr=0.3,0.1

Type RM Length L Ch R = 1,1020,156,156,156
BEGIN DESCRIPTION:
Elm 01 49 1019.56
END DESCRIPTION:
XS GIS Cut Line= 3
      1557495.45      6862043.95      1557205.53      6861981.45
      1556740.21      6862033.54
#Sta/Elev= 30
  4700.4 1751.41  4741.8 1750.54  4848.2 1746.97  4885.0 1746.04  4936.1 1743.81
  4941.7 1743.87  4947.3 1743.40  4966.8 1741.72  4977.1 1740.44  4985.9 1740.67
  4989.0 1740.30  4989.3 1739.80  4992.8 1739.80  4993.0 1740.30  4994.7 1741.48
  5006.7 1741.29  5011.8 1741.91  5017.6 1741.44  5037.8 1741.68  5047.8 1742.15
  5067.9 1742.18  5078.0 1742.89  5096.9 1742.50  5108.2 1742.91  5178.6 1743.28
  5198.8 1743.77  5208.8 1744.43  5239.0 1744.30  5395.4 1746.85  5465.2 1747.93
#Mann=5,-1,0
  4700.4   0.035       0  4947.3    0.07       0  4989.0    0.07       0
  4993.0    0.07       0  5395.4   0.035       0
Bank Sta=4989,4993
Exp/Cntr=0.3,0.1

Type RM Length L Ch R = 1,864,48,48,48
BEGIN DESCRIPTION:
Elm 01 49 905.22
END DESCRIPTION:
XS GIS Cut Line= 3
      1557511.05      6862021.36      1557160.28      6861834.51
      1556761.33      6861883.67
#Sta/Elev= 30
  4637.9 1751.35  4653.0 1751.08  4769.4 1747.00  4779.2 1746.97  4828.8 1745.04
  4850.7 1744.50  4867.0 1744.48  4872.7 1743.84  4877.5 1743.80  4894.7 1743.21
  4911.0 1743.00  4916.7 1743.26  4927.3 1741.55  4932.9 1741.24  4939.3 1739.72
  4993.2 1739.95  5027.8 1739.59  5028.1 1739.09  5031.6 1739.09  5031.8 1739.59
  5081.0 1739.91  5141.4 1739.61  5151.5 1741.64  5161.6 1742.44  5171.6 1742.60
  5181.6 1742.00  5186.6 1742.35  5252.2 1742.56  5430.2 1744.55  5437.3 1745.08
#Mann=4,-1,0
  4637.9   0.035       0  4877.5    0.07       0  5027.8    0.07       0
  5031.8    0.07       0
Bank Sta=5027.8,5031.8
Exp/Cntr=0.3,0.1

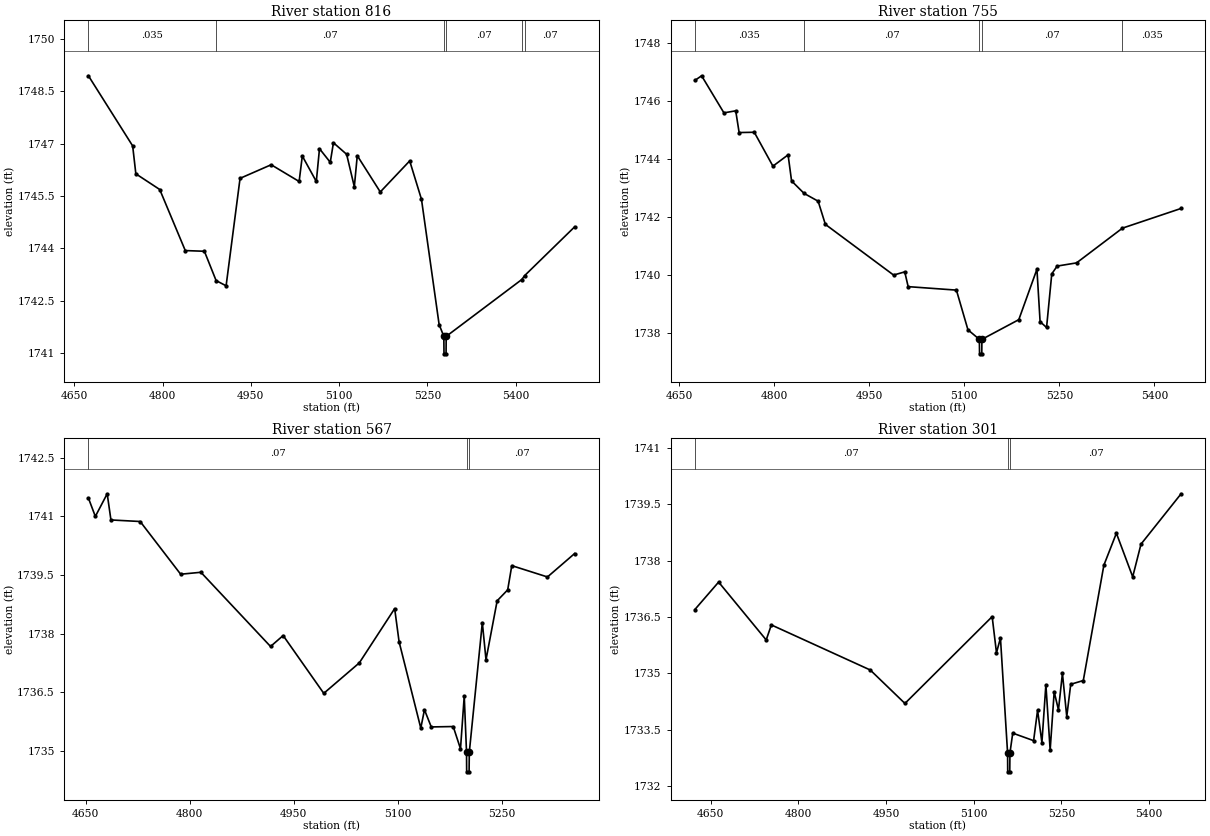
Type RM Length L Ch R = 1,816,61,61,61
BEGIN DESCRIPTION:
Elm 01 49 815.57
END DESCRIPTION:
XS GIS Cut Line= 4
      1557526.72      6861943.26      1557122.20      6861773.12
      1556946.76      6861771.65      1556758.66      6861869.46
#Sta/Elev= 30
  4674.0 1748.95  4749.2 1746.94  4754.6 1746.14  4795.2 1745.69  4838.6 1743.94
  4871.1 1743.92  4891.0 1743.08  4908.0 1742.93  4931.7 1746.01  4984.6 1746.40
  5032.1 1745.92  5037.5 1746.65  5061.3 1745.92  5066.7 1746.86  5085.0 1746.47
  5090.4 1747.03  5112.8 1746.70  5125.9 1745.77  5130.9 1746.66  5170.0 1745.62
  5220.0 1746.51  5240.0 1745.41  5270.0 1741.82  5278.0 1741.48  5278.3 1740.98
  5281.8 1740.98  5282.0 1741.48  5410.5 1743.11  5415.2 1743.22  5500.3 1744.62
#Mann=6,-1,0
  4674.0   0.035       0  4891.0    0.07       0  5278.0    0.07       0
  5282.0    0.07       0  5410.5   0.035       0  5415.2    0.07       0
Bank Sta=5278,5282
Exp/Cntr=0.3,0.1

Type RM Length L Ch R = 1,755,188,188,188
BEGIN DESCRIPTION:
Elm 01 49 671
END DESCRIPTION:
XS GIS Cut Line= 4
      1557554.82      6861889.42      1557176.25      6861733.69
      1557031.40      6861722.07      1556823.16      6861763.02
#Sta/Elev= 30
  4675.1 1746.72  4685.7 1746.88  4720.9 1745.60  4739.5 1745.67  4744.9 1744.92
  4768.8 1744.93  4798.2 1743.76  4822.1 1744.15  4827.6 1743.25  4847.3 1742.82
  4869.5 1742.55  4880.9 1741.75  4988.5 1740.00  5006.1 1740.11  5011.5 1739.60
  5087.6 1739.48  5105.8 1738.11  5123.8 1737.78  5124.1 1737.28  5127.6 1737.28
  5127.8 1737.78  5186.0 1738.46  5214.6 1740.20  5219.6 1738.39  5229.8 1738.19
  5238.0 1740.04  5246.5 1740.31  5277.1 1740.42  5349.5 1741.62  5442.0 1742.30
#Mann=5,-1,0
  4675.1   0.035       0  4847.3    0.07       0  5123.8    0.07       0
  5127.8    0.07       0  5349.5   0.035       0
Bank Sta=5123.8,5127.8
Exp/Cntr=0.3,0.1

Type RM Length L Ch R = 1,567,266,266,266
BEGIN DESCRIPTION:
Elm 01 49 510.96
END DESCRIPTION:
XS GIS Cut Line= 3
      1557584.18      6861713.80      1557238.36      6861568.97
      1556929.15      6861674.36
#Sta/Elev= 30
  4653.8 1741.47  4663.8 1741.00  4680.9 1741.58  4686.3 1740.91  4728.5 1740.87
  4786.9 1739.52  4816.1 1739.57  4916.6 1737.67  4934.8 1737.95  4993.4 1736.47
  5044.7 1737.25  5095.7 1738.64  5102.1 1737.79  5133.4 1735.58  5138.7 1736.05
  5148.5 1735.61  5180.2 1735.62  5190.7 1735.05  5196.1 1736.40  5199.4 1734.96
  5199.6 1734.46  5203.1 1734.46  5203.4 1734.96  5222.2 1738.28  5227.5 1737.33
  5243.6 1738.84  5258.8 1739.12  5264.7 1739.74  5316.2 1739.45  5355.4 1740.05
#Mann=3,-1,0
  4653.8    0.07       0  5199.4    0.07       0  5203.4    0.07       0
Bank Sta=5199.4,5203.4
Exp/Cntr=0.3,0.1

Type RM Length L Ch R = 1,301,0,0,0
BEGIN DESCRIPTION:
Elm 01 49 301.033
END DESCRIPTION:
XS GIS Cut Line= 3
      1557590.97      6861517.92      1557256.89      6861343.66
      1556923.98      6861653.67
#Sta/Elev= 30
  4623.2 1736.70  4663.8 1737.43  4745.2 1735.89  4754.0 1736.29  4923.2 1735.09
  4982.5 1734.20  5131.7 1736.51  5139.1 1735.55  5145.9 1735.94  5158.1 1732.88
  5158.3 1732.38  5161.8 1732.38  5162.1 1732.88  5166.9 1733.41  5202.6 1733.21
  5209.4 1734.02  5216.8 1733.16  5223.6 1734.70  5230.9 1732.96  5237.8 1734.51
  5245.1 1734.03  5251.9 1735.00  5259.3 1733.85  5266.1 1734.71  5287.6 1734.81
  5322.8 1737.88  5344.2 1738.73  5372.1 1737.57  5386.3 1738.44  5454.9 1739.78
#Mann=3,-1,0
  4623.2    0.07       0  5158.1    0.07       0  5162.1    0.07       0
Bank Sta=5158.1,5162.1
Exp/Cntr=0.3,0.1

Chan Stop Cuts=-1