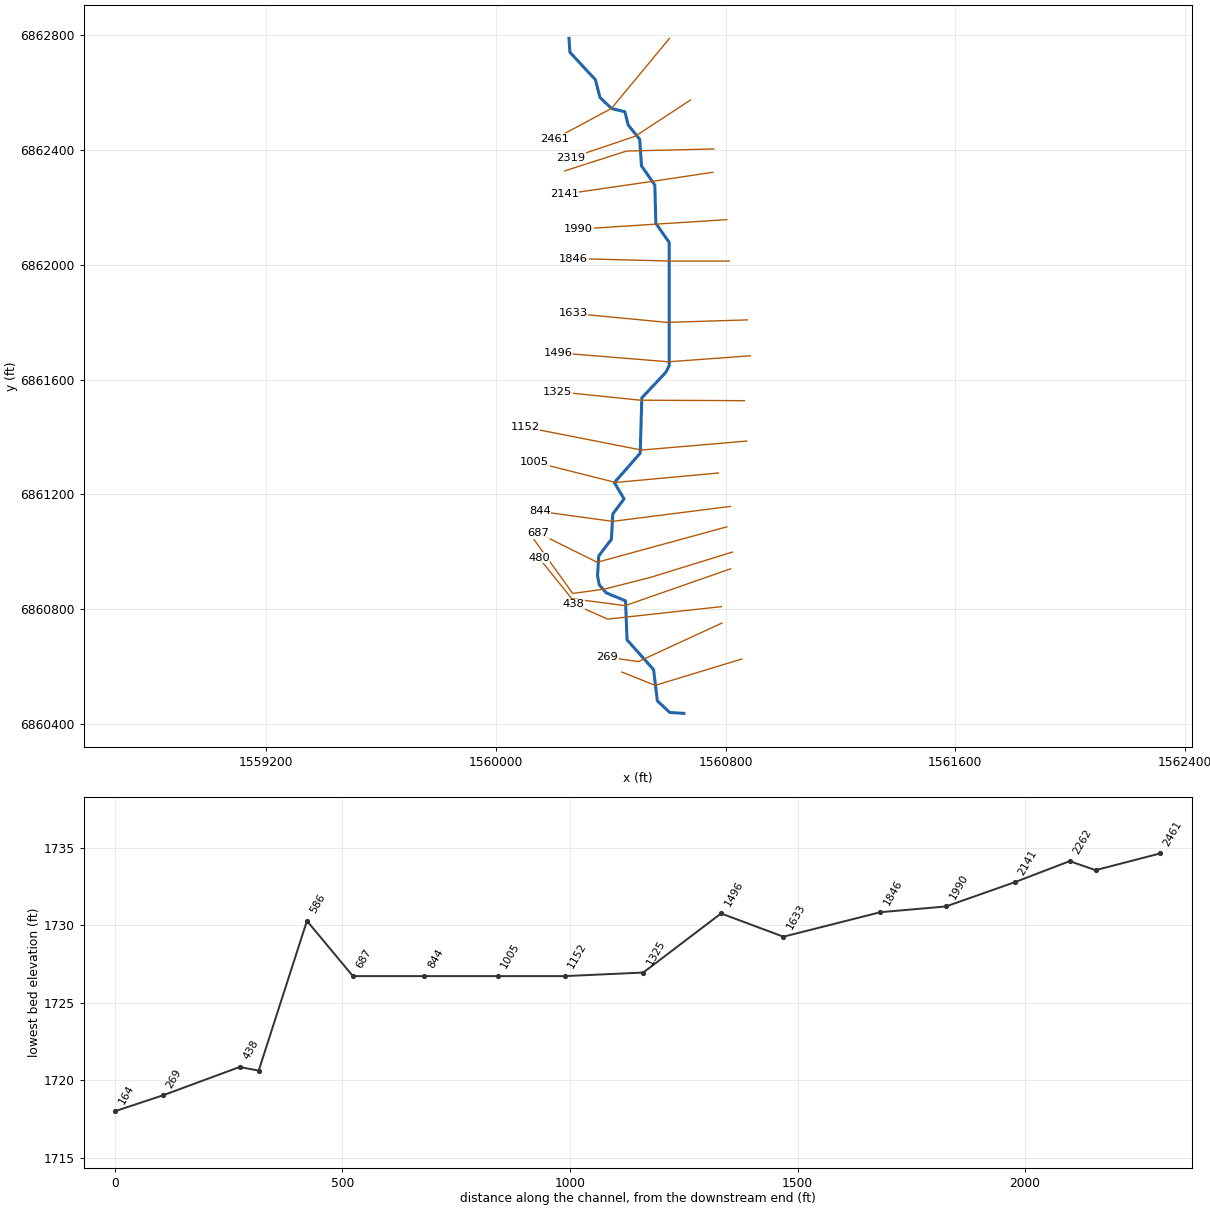
--- Elm 01 50.prj (project) ---

Proj Title=Elm 01 50 Base Level Engineering
Current Plan=p01
Default Exp/Contr=0.3,0.1
English Units
Geom File=g01
Flow File=f01
Plan File=p01
BEGIN DESCRIPTION:
Elm 01 50
END DESCRIPTION:

--- Elm 01 50.p01 (plan) ---

Plan Title=Multiple Run
Short Identifier=Multiple
Geom File=g01
Flow File=f01
Subcritical Flow
K Sum by GR= 0
Std Step Tol= 0.01
Critical Tol= 0.01
Num of Std Step Trials= 20
Max Error Tol= 0.3
Flow Tol Ratio= 0.001
Split Flow NTrial= 30
Split Flow Tol= 0.02
Split Flow Ratio= 0.02
Log Output Level= 0
Friction Slope Method= 1
Unsteady Friction Slope Method= 2
Unsteady Bridges Friction Slope Method= 1
Parabolic Critical Depth
Global Vel Dist=  1 , 1 , 1
Global Log Level= 0
CheckData=True
Encroach Param= -1, 0, 0, 0
BEGIN DESCRIPTION:
Multiple Run
END DESCRIPTION:

--- Elm 01 50.f01 (steady flow) ---

Flow Title=Multiple
Number of Profiles=7
Profile Names=10-year,25-year,50-year,1pct_min,100-year,1pct_plu,500-year
River Rch & RM= Elm 01 50,Reach-1,2461
      91     118     138     101     162     223     225
Boundary for River Rch & Prof#=Elm 01 50,Reach-1,1
Up Type=0
Dn Type=3
Dn Slope=0.005
Boundary for River Rch & Prof#=Elm 01 50,Reach-1,2
Up Type=0
Dn Type=3
Dn Slope=0.005
Boundary for River Rch & Prof#=Elm 01 50,Reach-1,3
Up Type=0
Dn Type=3
Dn Slope=0.005
Boundary for River Rch & Prof#=Elm 01 50,Reach-1,4
Up Type=0
Dn Type=3
Dn Slope=0.005
Boundary for River Rch & Prof#=Elm 01 50,Reach-1,5
Up Type=0
Dn Type=3
Dn Slope=0.005
Boundary for River Rch & Prof#=Elm 01 50,Reach-1,6
Up Type=0
Dn Type=3
Dn Slope=0.005
Boundary for River Rch & Prof#=Elm 01 50,Reach-1,7
Up Type=0
Dn Type=3
Dn Slope=0.005

--- Elm 01 50.g01 (geometry) ---

Geom Title=Existing Conditions

River Reach=Elm 01 50,Reach-1
Reach XY= 30
      1560255.00      6862788.00      1560258.29      6862739.36
      1560346.83      6862644.03      1560363.09      6862581.69
      1560402.80      6862543.89      1560449.38      6862532.38
      1560461.27      6862486.16      1560501.19      6862436.44
      1560507.36      6862343.98      1560553.77      6862277.49
      1560557.27      6862143.94      1560603.78      6862077.50
      1560603.94      6861648.44      1560591.60      6861624.69
      1560508.55      6861536.53      1560502.92      6861343.85
      1560413.01      6861241.33      1560446.71      6861184.78
      1560407.54      6861132.11      1560402.65      6861043.98
      1560358.70      6860986.40      1560354.31      6860917.85
      1560360.33      6860885.34      1560384.60      6860857.67
      1560451.89      6860829.68      1560457.08      6860693.87
      1560549.46      6860590.42      1560562.64      6860481.56
      1560605.99      6860441.12      1560655.00      6860438.00

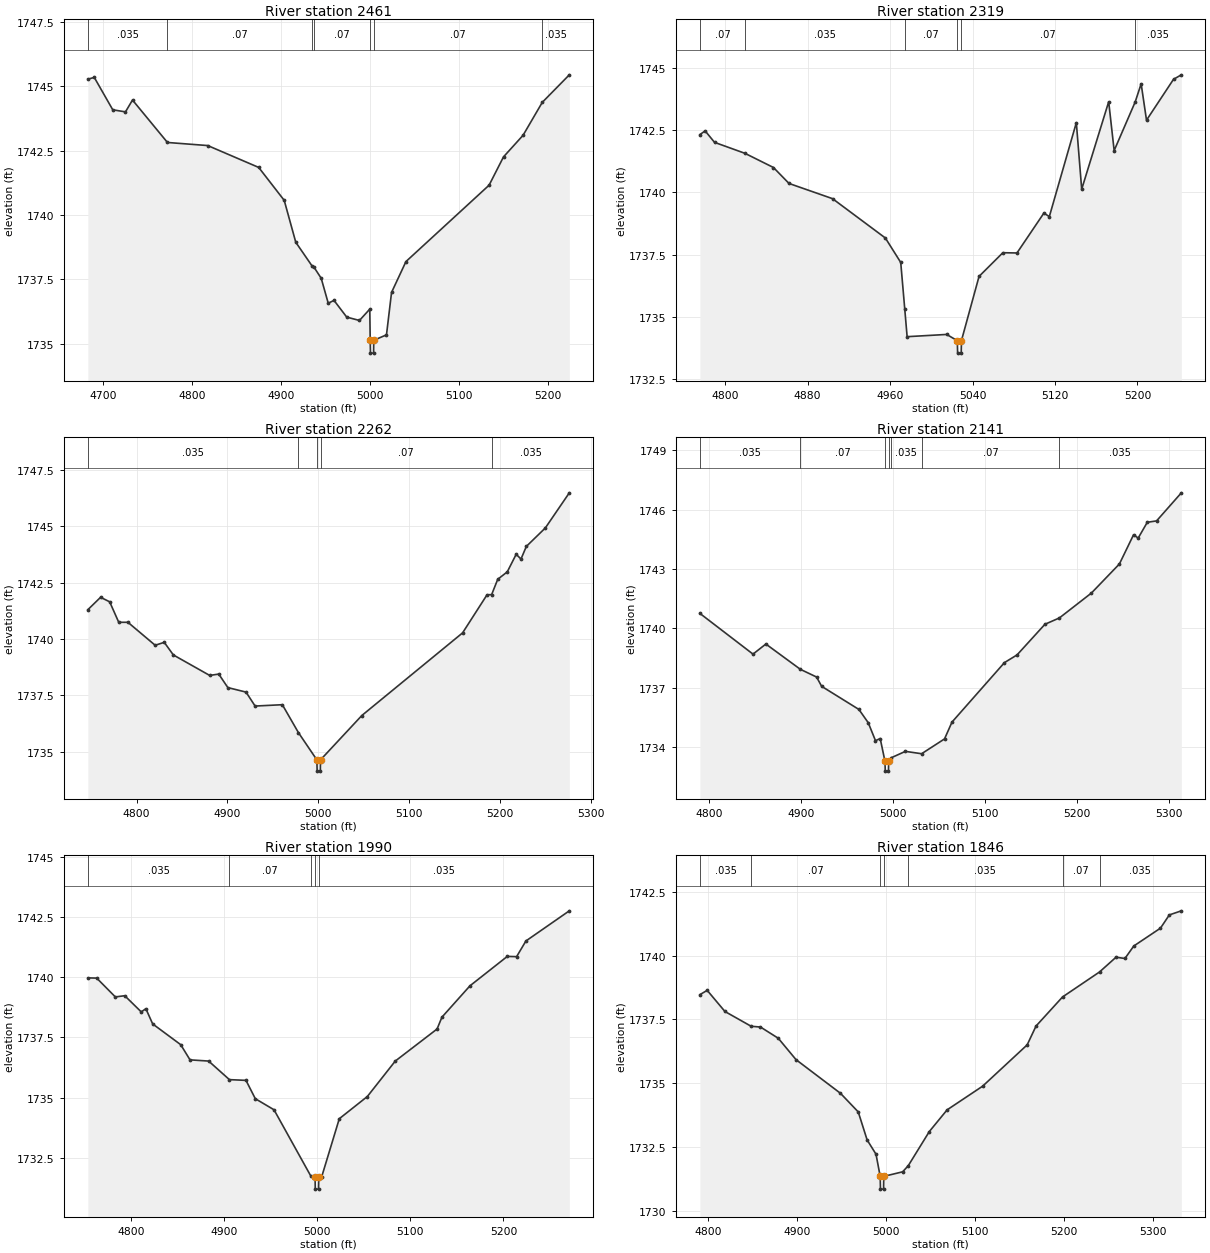
Type RM Length L Ch R = 1,2461,142,142,142
BEGIN DESCRIPTION:
Elm 01 50 2461.051
END DESCRIPTION:
XS GIS Cut Line= 3
      1560605.01      6862788.02      1560402.80      6862543.89
      1560204.96      6862437.98
#Sta/Elev= 30
  4683.0 1745.28  4690.2 1745.35  4711.0 1744.09  4725.3 1744.01  4733.2 1744.47
  4772.5 1742.82  4817.8 1742.70  4875.1 1741.85  4903.8 1740.57  4916.8 1738.94
  4935.3 1738.01  4937.1 1737.98  4945.4 1737.54  4953.3 1736.57  4959.8 1736.68
  4974.1 1736.03  4988.4 1735.90  5000.0 1736.34  5000.5 1735.13  5000.8 1734.63
  5004.3 1734.63  5004.5 1735.13  5018.8 1735.34  5024.5 1736.99  5040.7 1738.19
  5134.2 1741.16  5150.4 1742.26  5172.4 1743.10  5194.0 1744.38  5224.4 1745.45
#Mann=7,-1,0
  4683.0   0.035       0  4772.5    0.07       0  4935.3   0.035       0
  4937.1    0.07       0  5000.5    0.07       0  5004.5    0.07       0
  5194.0   0.035       0
Bank Sta=5000.5,5004.5
Exp/Cntr=0.3,0.1

Type RM Length L Ch R = 1,2319,57,57,57
BEGIN DESCRIPTION:
Elm 01 50 2333.51
END DESCRIPTION:
XS GIS Cut Line= 3
      1560678.00      6862573.30      1560485.30      6862447.05
      1560260.95      6862371.19
#Sta/Elev= 30
  4775.4 1742.32  4780.5 1742.47  4789.6 1742.01  4819.1 1741.57  4846.8 1741.00
  4861.9 1740.36  4904.1 1739.75  4955.4 1738.17  4970.3 1737.19  4974.2 1735.32
  4976.5 1734.21  5014.9 1734.30  5025.2 1734.05  5025.5 1733.55  5029.0 1733.55
  5029.2 1734.05  5046.3 1736.63  5069.4 1737.58  5083.1 1737.57  5109.2 1739.17
  5114.5 1739.03  5140.7 1742.80  5145.9 1740.13  5172.1 1743.64  5177.4 1741.68
  5197.8 1743.63  5203.6 1744.36  5208.8 1742.90  5235.0 1744.54  5242.6 1744.72
#Mann=6,-1,0
  4775.4    0.07       0  4819.1   0.035       0  4974.2    0.07       0
  5025.2    0.07       0  5029.2    0.07       0  5197.8   0.035       0
Bank Sta=5025.2,5029.2
Exp/Cntr=0.3,0.1

Type RM Length L Ch R = 1,2262,121,121,121
BEGIN DESCRIPTION:
Elm 01 50 10.0
END DESCRIPTION:
XS GIS Cut Line= 3
      1560759.04      6862402.89      1560455.01      6862395.59
      1560239.95      6862326.51
#Sta/Elev= 30
  4746.4 1741.30  4760.4 1741.85  4770.4 1741.65  4780.4 1740.74  4790.5 1740.74
  4820.5 1739.72  4830.5 1739.85  4840.5 1739.29  4880.5 1738.38  4890.5 1738.44
  4900.5 1737.84  4920.5 1737.64  4930.5 1737.02  4960.5 1737.08  4978.2 1735.84
  4998.5 1734.63  4998.8 1734.13  5002.3 1734.13  5002.5 1734.63  5048.0 1736.60
  5158.9 1740.27  5185.8 1741.96  5190.9 1741.97  5197.6 1742.65  5208.1 1742.98
  5217.9 1743.76  5223.2 1743.55  5229.1 1744.11  5250.0 1744.93  5276.4 1746.49
#Mann=5,-1,0
  4746.4   0.035       0  4978.2    0.07       0  4998.5    0.07       0
  5002.5    0.07       0  5190.9   0.035       0
Bank Sta=4998.5,5002.5
Exp/Cntr=0.3,0.1

Type RM Length L Ch R = 1,2141,151,151,151
BEGIN DESCRIPTION:
Elm 01 50 2140.97
END DESCRIPTION:
XS GIS Cut Line= 3
      1560755.88      6862321.73      1560547.55      6862290.48
      1560238.36      6862245.57
#Sta/Elev= 30
  4790.1 1740.75  4847.8 1738.69  4861.8 1739.20  4899.3 1737.92  4916.9 1737.53
  4922.4 1737.06  4962.9 1735.89  4973.0 1735.22  4980.9 1734.31  4986.0 1734.42
  4991.2 1733.27  4991.5 1732.77  4995.0 1732.77  4995.2 1733.27  4997.7 1733.44
  5013.4 1733.77  5031.0 1733.65  5055.9 1734.40  5064.0 1735.25  5121.0 1738.26
  5134.7 1738.65  5165.0 1740.20  5180.7 1740.52  5215.5 1741.78  5245.9 1743.25
  5261.3 1744.73  5266.3 1744.56  5276.2 1745.36  5286.3 1745.43  5313.2 1746.85
#Mann=7,-1,0
  4790.1   0.035       0  4899.3    0.07       0  4991.2   0.035       0
  4995.2    0.07       0  4997.7   0.035       0  5031.0    0.07       0
  5180.7   0.035       0
Bank Sta=4991.2,4995.2
Exp/Cntr=0.3,0.1

Type RM Length L Ch R = 1,1990,144,144,144
BEGIN DESCRIPTION:
Elm 01 50 1990.08
END DESCRIPTION:
XS GIS Cut Line= 3
      1560804.48      6862156.80      1560557.96      6862141.17
      1560288.52      6862123.90
#Sta/Elev= 30
  4753.8 1739.97  4763.3 1739.96  4783.3 1739.18  4793.4 1739.23  4811.1 1738.56
  4816.1 1738.69  4823.4 1738.06  4853.5 1737.20  4863.5 1736.57  4883.5 1736.52
  4905.8 1735.75  4923.6 1735.72  4933.6 1734.96  4953.7 1734.50  4993.1 1731.76
  4997.8 1731.71  4998.0 1731.21  5001.5 1731.21  5001.8 1731.71  5004.8 1731.71
  5023.8 1734.13  5053.9 1735.05  5083.9 1736.52  5128.8 1737.85  5134.0 1738.34
  5164.1 1739.64  5204.2 1740.86  5214.2 1740.85  5224.2 1741.50  5270.8 1742.75
#Mann=5,-1,0
  4753.8   0.035       0  4905.8    0.07       0  4993.1   0.035       0
  4997.8   0.035       0  5001.8   0.035       0
Bank Sta=4997.8,5001.8
Exp/Cntr=0.3,0.1

Type RM Length L Ch R = 1,1846,213,213,213
BEGIN DESCRIPTION:
Elm 01 50 1846.48
END DESCRIPTION:
XS GIS Cut Line= 3
      1560813.20      6862012.70      1560606.58      6862012.70
      1560271.52      6862021.38
#Sta/Elev= 30
  4790.6 1738.47  4798.8 1738.64  4818.8 1737.81  4848.3 1737.23  4858.8 1737.20
  4878.8 1736.76  4898.8 1735.92  4948.8 1734.60  4968.8 1733.87  4978.8 1732.77
  4988.8 1732.21  4993.5 1731.34  4993.8 1730.84  4997.3 1730.84  4997.5 1731.34
  5018.8 1731.52  5025.1 1731.76  5048.8 1733.10  5068.8 1733.95  5108.8 1734.88
  5158.9 1736.50  5168.9 1737.24  5198.7 1738.38  5240.3 1739.36  5258.9 1739.94
  5268.9 1739.89  5278.9 1740.38  5308.9 1741.08  5318.9 1741.60  5332.4 1741.76
#Mann=7,-1,0
  4790.6   0.035       0  4848.3    0.07       0  4993.5    0.07       0
  4997.5    0.07       0  5025.1   0.035       0  5198.7    0.07       0
  5240.3   0.035       0
Bank Sta=4993.5,4997.5
Exp/Cntr=0.3,0.1

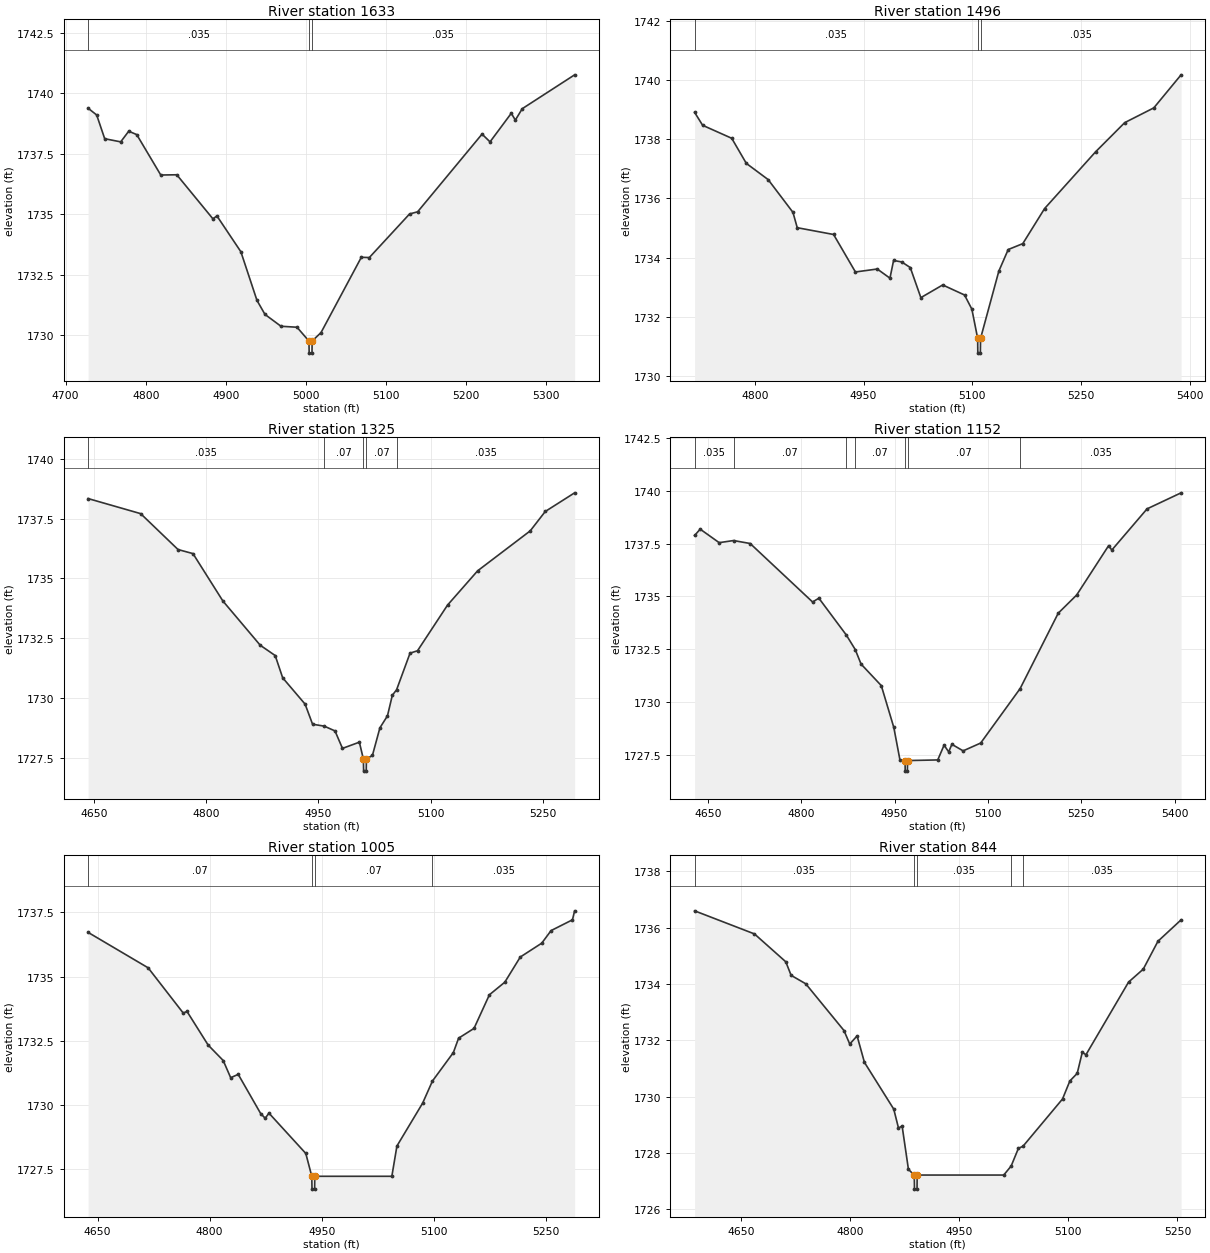
Type RM Length L Ch R = 1,1633,137,137,137
BEGIN DESCRIPTION:
Elm 01 50 1633.1
END DESCRIPTION:
XS GIS Cut Line= 3
      1560875.66      6861807.84      1560596.16      6861799.16
      1560269.88      6861830.40
#Sta/Elev= 30
  4728.1 1739.38  4738.8 1739.10  4748.8 1738.12  4768.8 1737.99  4778.8 1738.43
  4788.8 1738.29  4818.8 1736.62  4838.8 1736.63  4883.9 1734.81  4888.9 1734.93
  4918.8 1733.45  4938.9 1731.44  4948.9 1730.86  4968.9 1730.37  4988.9 1730.33
  5003.8 1729.76  5004.1 1729.26  5007.6 1729.26  5007.8 1729.76  5018.9 1730.11
  5069.2 1733.22  5079.2 1733.21  5129.4 1735.01  5139.5 1735.10  5219.9 1738.31
  5229.9 1737.99  5256.4 1739.17  5261.5 1738.89  5270.1 1739.36  5335.5 1740.76
#Mann=3,-1,0
  4728.1   0.035       0  5003.8   0.035       0  5007.8   0.035       0
Bank Sta=5003.8,5007.8
Exp/Cntr=0.3,0.1

Type RM Length L Ch R = 1,1496,171,171,171
BEGIN DESCRIPTION:
Elm 01 50 1495.9
END DESCRIPTION:
XS GIS Cut Line= 3
      1560886.09      6861682.84      1560601.37      6861662.01
      1560217.51      6861693.13
#Sta/Elev= 30
  4717.1 1738.92  4728.2 1738.48  4768.3 1738.04  4788.4 1737.19  4818.5 1736.64
  4852.7 1735.53  4858.6 1735.01  4908.7 1734.78  4938.8 1733.51  4968.9 1733.61
  4986.4 1733.30  4991.4 1733.90  5002.6 1733.85  5014.4 1733.66  5029.0 1732.64
  5059.1 1733.07  5089.2 1732.73  5099.3 1732.25  5107.3 1731.26  5107.5 1730.76
  5111.0 1730.76  5111.3 1731.26  5136.5 1733.54  5149.4 1734.27  5169.5 1734.47
  5199.6 1735.66  5269.8 1737.58  5310.0 1738.57  5350.1 1739.07  5387.7 1740.19
#Mann=3,-1,0
  4717.1   0.035       0  5107.3   0.035       0  5111.3   0.035       0
Bank Sta=5107.3,5111.3
Exp/Cntr=0.3,0.1

Type RM Length L Ch R = 1,1325,173,173,173
BEGIN DESCRIPTION:
Elm 01 50 1325.39
END DESCRIPTION:
XS GIS Cut Line= 3
      1560865.30      6861526.59      1560502.41      6861528.33
      1560215.92      6861557.84
#Sta/Elev= 30
  4641.9 1738.34  4712.2 1737.71  4762.2 1736.21  4782.2 1736.04  4822.2 1734.06
  4872.2 1732.21  4892.2 1731.78  4902.2 1730.85  4932.2 1729.75  4942.2 1728.91
  4957.8 1728.83  4972.2 1728.63  4982.2 1727.90  5004.8 1728.16  5010.2 1727.45
  5010.5 1726.95  5014.0 1726.95  5014.2 1727.45  5022.3 1727.61  5032.3 1728.76
  5042.4 1729.26  5048.9 1730.12  5054.6 1730.35  5072.6 1731.88  5082.6 1731.98
  5122.8 1733.89  5163.0 1735.32  5233.4 1736.99  5253.5 1737.80  5292.8 1738.58
#Mann=5,-1,0
  4641.9   0.035       0  4957.8    0.07       0  5010.2    0.07       0
  5014.2    0.07       0  5054.6   0.035       0
Bank Sta=5010.2,5014.2
Exp/Cntr=0.3,0.1

Type RM Length L Ch R = 1,1152,147,147,147
BEGIN DESCRIPTION:
Elm 01 50 1152.25
END DESCRIPTION:
XS GIS Cut Line= 3
      1560873.95      6861385.97      1560507.62      6861354.71
      1560101.35      6861434.58
#Sta/Elev= 30
  4628.6 1737.88  4637.6 1738.18  4668.1 1737.54  4691.2 1737.64  4717.9 1737.50
  4818.2 1734.73  4828.3 1734.91  4872.3 1733.17  4886.7 1732.48  4896.1 1731.79
  4928.6 1730.77  4948.7 1728.79  4958.7 1727.23  4966.8 1727.22  4967.0 1726.72
  4970.5 1726.72  4970.8 1727.22  5019.3 1727.25  5029.5 1727.95  5036.9 1727.63
  5042.0 1727.99  5060.1 1727.68  5088.3 1728.05  5151.7 1730.63  5212.9 1734.20
  5242.5 1735.06  5293.9 1737.40  5299.0 1737.19  5355.6 1739.14  5410.3 1739.90
#Mann=7,-1,0
  4628.6   0.035       0  4691.2    0.07       0  4872.3   0.035       0
  4886.7    0.07       0  4966.8    0.07       0  4970.8    0.07       0
  5151.7   0.035       0
Bank Sta=4966.8,4970.8
Exp/Cntr=0.3,0.1

Type RM Length L Ch R = 1,1005,161,161,161
BEGIN DESCRIPTION:
Elm 01 50 1005.19
END DESCRIPTION:
XS GIS Cut Line= 3
      1560774.93      6861274.85      1560417.34      6861241.87
      1560134.46      6861313.02
#Sta/Elev= 30
  4637.4 1736.72  4717.7 1735.34  4764.6 1733.58  4769.7 1733.64  4798.0 1732.33
  4818.1 1731.73  4828.1 1731.06  4838.2 1731.19  4868.3 1729.66  4874.3 1729.48
  4879.3 1729.68  4928.6 1728.11  4936.6 1727.22  4936.9 1726.72  4940.4 1726.72
  4940.6 1727.22  5043.7 1727.22  5050.5 1728.40  5084.9 1730.07  5098.0 1730.93
  5126.0 1732.04  5133.0 1732.60  5153.6 1732.98  5174.2 1734.29  5194.8 1734.78
  5215.5 1735.76  5244.2 1736.30  5256.7 1736.79  5285.3 1737.21  5288.2 1737.56
#Mann=4,-1,0
  4637.4    0.07       0  4936.6    0.07       0  4940.6    0.07       0
  5098.0   0.035       0
Bank Sta=4936.6,4940.6
Exp/Cntr=0.3,0.1

Type RM Length L Ch R = 1,844,157,157,157
BEGIN DESCRIPTION:
Elm 01 50 844.28
END DESCRIPTION:
XS GIS Cut Line= 3
      1560816.62      6861158.53      1560406.92      6861106.45
      1560153.48      6861141.17
#Sta/Elev= 30
  4586.2 1736.60  4668.5 1735.78  4711.6 1734.79  4718.9 1734.31  4739.0 1734.01
  4791.6 1732.35  4799.5 1731.87  4809.6 1732.16  4819.7 1731.22  4860.0 1729.56
  4866.5 1728.89  4871.5 1728.96  4880.2 1727.42  4888.2 1727.22  4888.5 1726.72
  4892.0 1726.72  4892.2 1727.22  5011.2 1727.22  5021.4 1727.54  5031.4 1728.17
  5037.6 1728.24  5092.0 1729.92  5102.1 1730.56  5112.2 1730.83  5119.2 1731.58
  5124.2 1731.49  5182.8 1734.07  5203.0 1734.53  5223.2 1735.52  5255.0 1736.28
#Mann=5,-1,0
  4586.2   0.035       0  4888.2   0.035       0  4892.2   0.035       0
  5021.4    0.07       0  5037.6   0.035       0
Bank Sta=4888.2,4892.2
Exp/Cntr=0.3,0.1

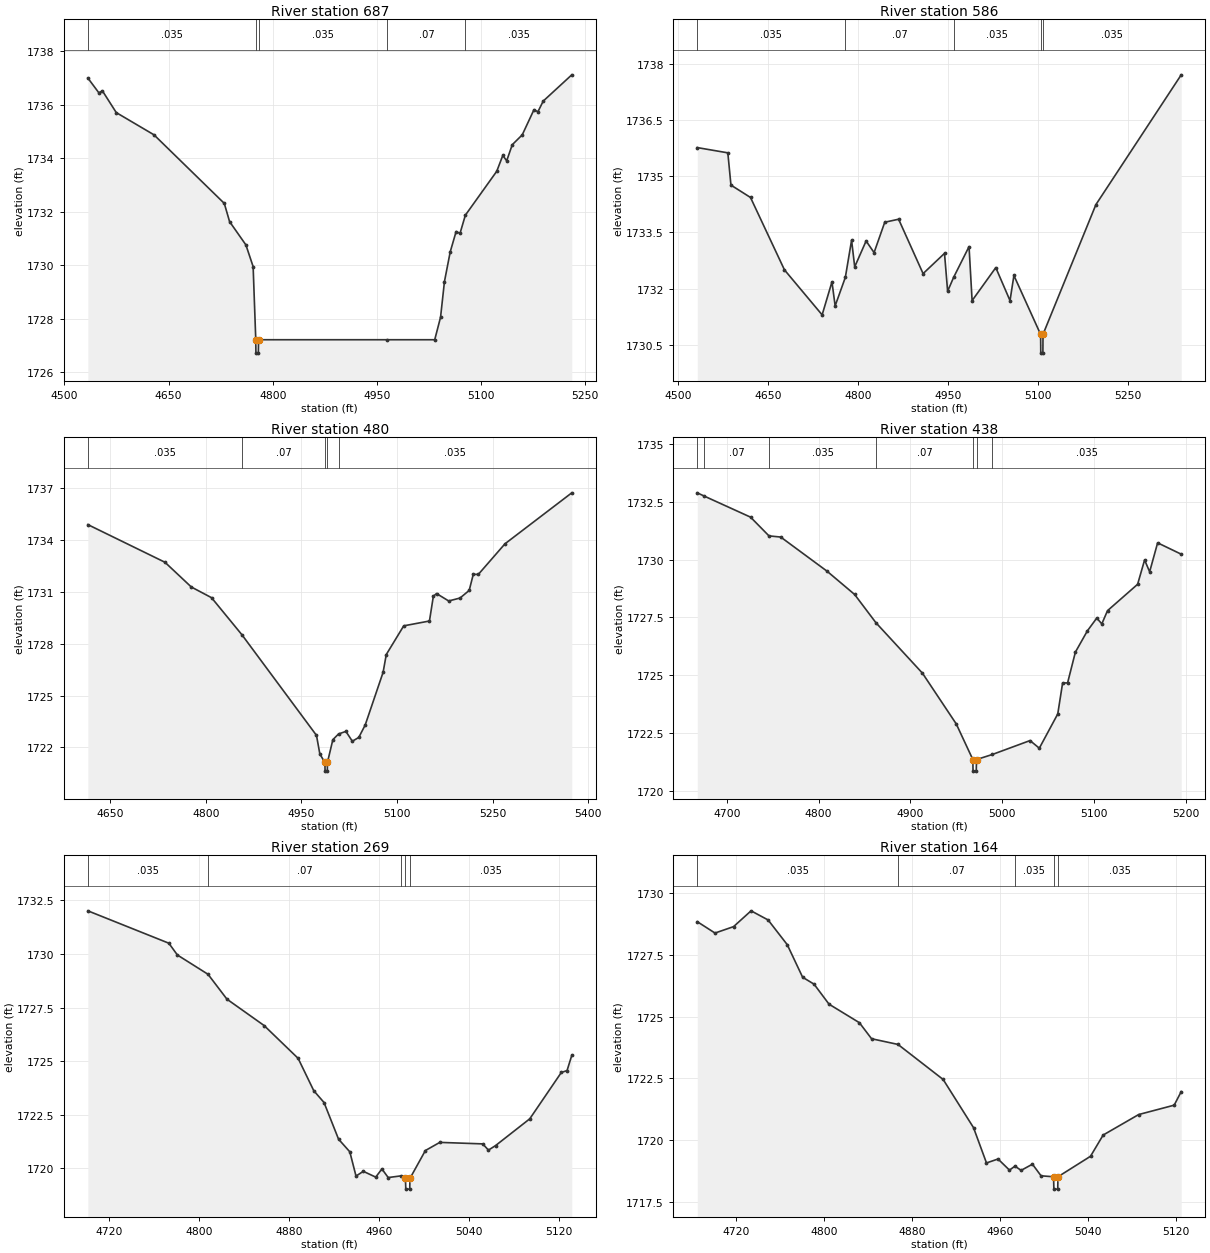
Type RM Length L Ch R = 1,687,101,101,101
BEGIN DESCRIPTION:
Elm 01 50 686.68
END DESCRIPTION:
XS GIS Cut Line= 3
      1560804.49      6861087.35      1560353.10      6860964.09
      1560148.22      6861065.67
#Sta/Elev= 30
  4533.9 1736.99  4549.7 1736.44  4554.9 1736.51  4574.8 1735.70  4629.1 1734.87
  4730.3 1732.31  4737.9 1731.63  4761.4 1730.76  4771.8 1729.95  4775.6 1727.22
  4775.8 1726.72  4779.3 1726.72  4779.6 1727.22  4964.9 1727.22  5033.2 1727.22
  5041.6 1728.06  5047.2 1729.39  5055.5 1730.50  5064.0 1731.26  5069.6 1731.19
  5077.3 1731.87  5122.5 1733.51  5131.2 1734.10  5136.8 1733.90  5144.8 1734.50
  5159.2 1734.87  5176.1 1735.81  5181.7 1735.73  5189.4 1736.13  5230.5 1737.11
#Mann=5,-1,0
  4533.9   0.035       0  4775.6    0.07       0  4779.6   0.035       0
  4964.9    0.07       0  5077.3   0.035       0
Bank Sta=4775.6,4779.6
Exp/Cntr=0.3,0.1

Type RM Length L Ch R = 1,586,106,106,106
BEGIN DESCRIPTION:
Elm 01 50 587.096
END DESCRIPTION:
XS GIS Cut Line= 5
      1560823.83      6860999.49      1560540.60      6860912.01
      1560377.41      6860870.34      1560267.91      6860855.56
      1560132.96      6861043.47
#Sta/Elev= 30
  4531.6 1735.76  4582.5 1735.62  4587.7 1734.76  4620.3 1734.43  4676.9 1732.50
  4739.7 1731.30  4756.1 1732.18  4761.4 1731.54  4778.4 1732.30  4788.8 1733.29
  4794.0 1732.58  4813.0 1733.27  4826.3 1732.96  4844.1 1733.77  4867.2 1733.85
  4908.0 1732.40  4943.7 1732.94  4948.9 1731.93  4958.9 1732.30  4984.6 1733.12
  4989.7 1731.68  5029.2 1732.56  5052.9 1731.68  5059.4 1732.35  5103.9 1730.78
  5104.2 1730.28  5107.7 1730.28  5107.9 1730.78  5196.1 1734.24  5338.3 1737.70
#Mann=5,-1,0
  4531.6   0.035       0  4778.4    0.07       0  4958.9   0.035       0
  5103.9   0.035       0  5107.9   0.035       0
Bank Sta=5103.9,5107.9
Exp/Cntr=0.3,0.1

Type RM Length L Ch R = 1,480,42,42,42
BEGIN DESCRIPTION:
Elm 01 50 479.65
END DESCRIPTION:
XS GIS Cut Line= 4
      1560818.34      6860941.51      1560450.33      6860813.05
      1560264.56      6860837.35      1560149.97      6860979.73
#Sta/Elev= 30
  4614.6 1734.90  4735.7 1732.72  4777.0 1731.29  4808.8 1730.67  4856.6 1728.52
  4973.6 1722.70  4978.9 1721.62  4986.8 1721.13  4987.1 1720.63  4990.6 1720.63
  4990.8 1721.13  4999.3 1722.45  5008.2 1722.78  5019.8 1722.93  5029.9 1722.36
  5040.0 1722.58  5050.1 1723.30  5078.2 1726.35  5083.2 1727.38  5110.6 1729.04
  5151.0 1729.32  5157.1 1730.75  5162.1 1730.91  5181.2 1730.48  5199.0 1730.65
  5213.4 1731.09  5219.8 1732.02  5227.8 1732.02  5269.6 1733.79  5374.5 1736.74
#Mann=5,-1,0
  4614.6   0.035       0  4856.6    0.07       0  4986.8    0.07       0
  4990.8    0.07       0  5008.2   0.035       0
Bank Sta=4986.8,4990.8
Exp/Cntr=0.3,0.1

Type RM Length L Ch R = 1,438,169,169,169
BEGIN DESCRIPTION:
Elm 01 50 438.43
END DESCRIPTION:
XS GIS Cut Line= 3
      1560785.38      6860809.57      1560389.56      6860766.17
      1560271.53      6860818.25
#Sta/Elev= 30
  4667.8 1732.88  4675.3 1732.74  4725.8 1731.83  4745.9 1731.02  4758.7 1730.97
  4809.0 1729.50  4839.2 1728.49  4862.4 1727.27  4913.1 1725.09  4949.9 1722.90
  4968.0 1721.36  4968.2 1720.86  4971.7 1720.86  4972.0 1721.36  4989.3 1721.58
  5030.3 1722.18  5040.4 1721.85  5060.5 1723.33  5065.8 1724.67  5071.2 1724.67
  5079.7 1726.00  5092.8 1726.92  5103.0 1727.47  5108.5 1727.22  5114.7 1727.79
  5147.5 1728.93  5155.1 1729.98  5160.6 1729.47  5169.3 1730.72  5195.0 1730.23
#Mann=7,-1,0
  4667.8   0.035       0  4675.3    0.07       0  4745.9   0.035       0
  4862.4    0.07       0  4968.0   0.035       0  4972.0    0.07       0
  4989.3   0.035       0
Bank Sta=4968,4972
Exp/Cntr=0.3,0.1

Type RM Length L Ch R = 1,269,105,105,105
BEGIN DESCRIPTION:
Elm 01 50 286.32
END DESCRIPTION:
XS GIS Cut Line= 3
      1560787.15      6860752.29      1560496.14      6860618.08
      1560388.07      6860633.94
#Sta/Elev= 30
  4701.4 1732.01  4773.3 1730.50  4780.9 1729.95  4808.1 1729.05  4824.9 1727.89
  4857.9 1726.66  4888.1 1725.13  4902.0 1723.62  4911.1 1723.07  4924.0 1721.36
  4934.0 1720.77  4939.5 1719.64  4946.0 1719.86  4957.0 1719.59  4962.5 1719.97
  4968.1 1719.57  4979.7 1719.65  4983.4 1719.53  4983.7 1719.03  4987.2 1719.03
  4987.4 1719.53  5001.1 1720.83  5013.9 1721.21  5052.0 1721.14  5057.1 1720.85
  5063.4 1721.06  5093.8 1722.31  5121.8 1724.47  5126.9 1724.56  5131.1 1725.27
#Mann=5,-1,0
  4701.4   0.035       0  4808.1    0.07       0  4979.7   0.035       0
  4983.4   0.035       0  4987.4   0.035       0
Bank Sta=4983.4,4987.4
Exp/Cntr=0.3,0.1

Type RM Length L Ch R = 1,164,0,0,0
BEGIN DESCRIPTION:
Elm 01 50 164.019
END DESCRIPTION:
XS GIS Cut Line= 3
      1560856.61      6860627.29      1560555.17      6860535.53
      1560439.05      6860581.80
#Sta/Elev= 30
  4684.9 1728.84  4701.0 1728.38  4717.9 1728.64  4733.8 1729.28  4749.3 1728.91
  4766.7 1727.91  4780.7 1726.59  4791.1 1726.31  4804.7 1725.50  4832.3 1724.75
  4843.4 1724.10  4867.4 1723.87  4908.5 1722.45  4936.1 1720.50  4947.9 1719.07
  4958.4 1719.23  4968.8 1718.78  4973.8 1718.94  4979.4 1718.77  4989.7 1719.02
  4997.5 1718.55  5008.9 1718.51  5009.2 1718.01  5012.7 1718.01  5012.9 1718.51
  5042.5 1719.34  5054.0 1720.20  5086.3 1721.03  5118.6 1721.41  5125.0 1721.96
#Mann=5,-1,0
  4684.9   0.035       0  4867.4    0.07       0  4973.8   0.035       0
  5008.9   0.035       0  5012.9   0.035       0
Bank Sta=5008.9,5012.9
Exp/Cntr=0.3,0.1

Chan Stop Cuts=-1