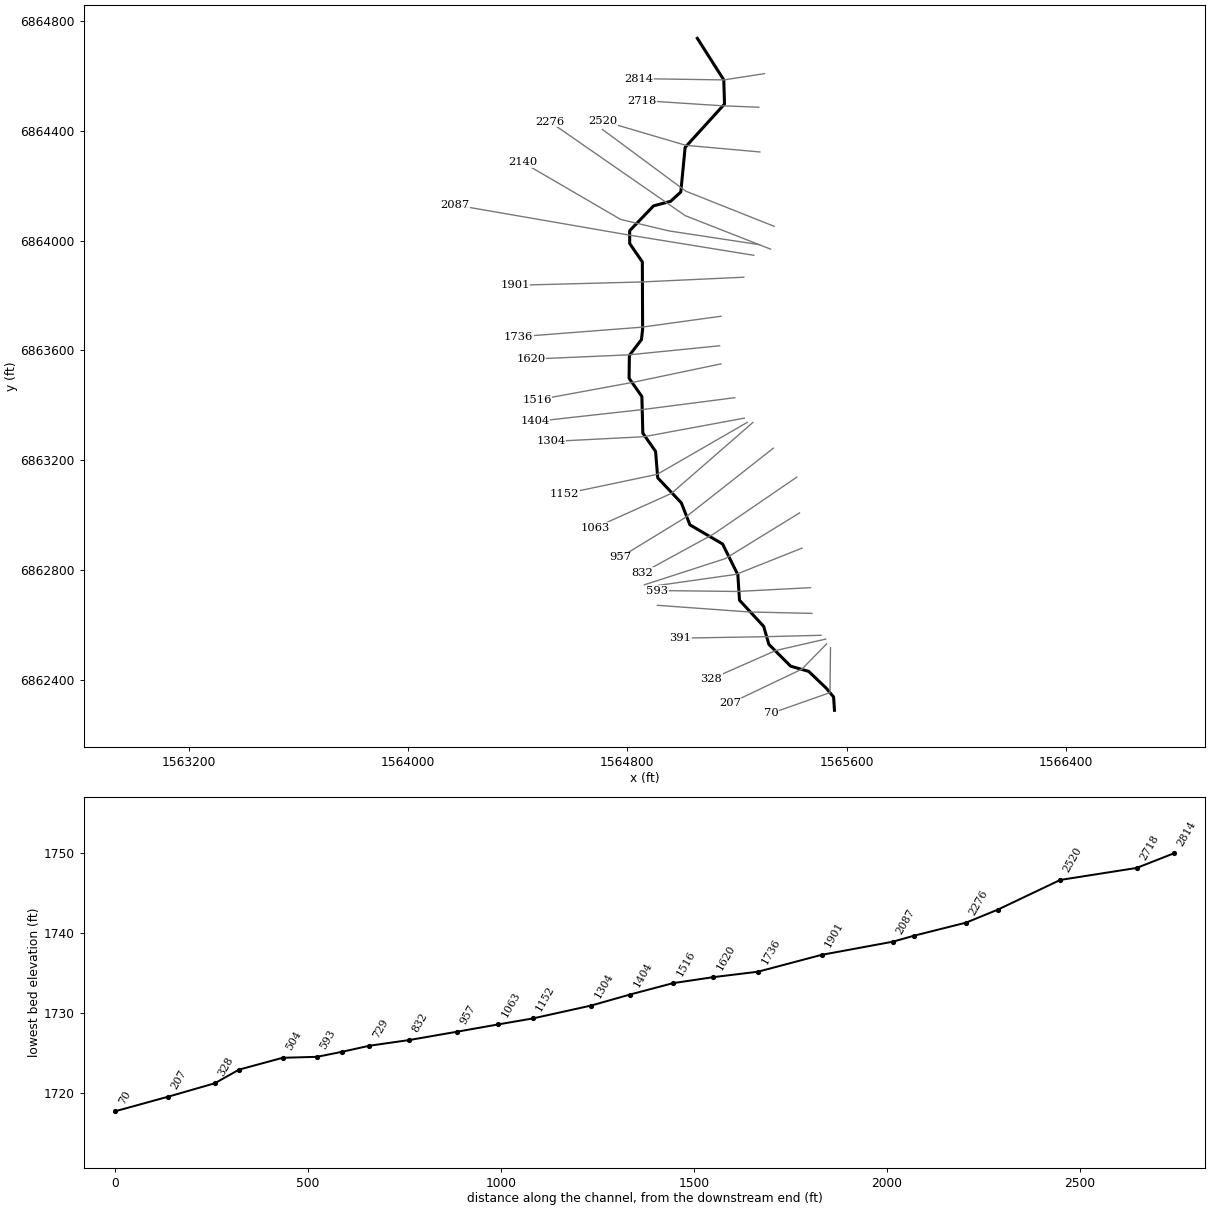
--- Elm 01 52.prj (project) ---

Proj Title=Elm 01 52 Base Level Engineering
Current Plan=p01
Default Exp/Contr=0.3,0.1
English Units
Geom File=g01
Flow File=f01
Plan File=p01
Y Axis Title=Elevation
X Axis Title(PF)=Main Channel Distance
X Axis Title(XS)=Station
BEGIN DESCRIPTION:
Elm 01 52
END DESCRIPTION:
DSS Export Rating Curves= 0
DSS Export Rating Curve Sorted= 0
DSS Export Volume Flow Curves= 0
DXF OffsetX= 0
DXF OffsetY= 0
DXF ScaleX= 1
DXF ScaleY= 10

--- Elm 01 52.p01 (plan) ---

Plan Title=Multiple Run
Program Version=4.10
Short Identifier=Multiple
Geom File=g01
Flow File=f01
Subcritical Flow
K Sum by GR= 0
Std Step Tol= 0.01
Critical Tol= 0.01
Num of Std Step Trials= 20
Max Error Tol= 0.3
Flow Tol Ratio= 0.001
Split Flow NTrial= 30
Split Flow Tol= 0.02
Split Flow Ratio= 0.02
Log Output Level= 0
Friction Slope Method= 1
Unsteady Friction Slope Method= 2
Unsteady Bridges Friction Slope Method= 1
Parabolic Critical Depth
Global Vel Dist= 1 , 1 , 1
Global Log Level= 0
CheckData=True
Encroach Param=-1 ,0,0, 0
BEGIN DESCRIPTION:
Multiple Run
END DESCRIPTION:
Computation Interval=1HOUR
Output Interval=1HOUR
Run HTab= 0
Run UNet= 0
Run PostProcess= 0
Run WQNet= 0
UNET Theta= 1
UNET Theta Warmup= 1
UNET ZTol= 0.02
UNET ZSATol= 0.05
UNET MxIter= 20
UNET MaxInSteps= 0
UNET DtIC= 0
UNET DtMin= 0
UNET MaxCRTS= 20
UNET WFStab= 2
UNET SFStab= 1
UNET WFX= 1
UNET SFX= 1
UNET DSS MLevel= 4
UNET DZMax Abort= 100
UNET Convert EG Bridges= 0
UNET Use Existing IB Tables=-1
UNET Froude Reduction=False
UNET Froude Limit= 1
UNET Froude Power= 10
UNET Time Slicing=0,0, 5
UNET Junction Losses=0
Instantaneous Interval=1HOUR
Write IC File= 0
Write IC File at Sim End=0
Echo Input=False
Echo Parameters=False
Echo Output=False
Write Detailed= 0
WQ AD Non Conservative
WQ ULTIMATE=-1
WQ Max Comp Step=1HOUR
WQ Output Interval=15MIN
WQ Output Selected Increments= 0
WQ Output face flow=0
WQ Output face velocity=0
WQ Output face area=0
WQ Output face dispersion=0
WQ Output cell volume=0
WQ Output cell surface area=0
WQ Output cell continuity=0
WQ Output cumulative cell continuity=0
WQ Output face conc=0
WQ Output face dconc_dx=0
WQ Output face courant=0
WQ Output face peclet=0
WQ Output face adv mass=0
WQ Output face disp mass=0
WQ Output cell mass=0
WQ Output cell source sink temp=0
WQ Output cell source sink nsm=0
WQ Output MaxMinRange=-1
WQ Daily Max Min Mean=-1
WQ Daily Range=0
WQ Daily Time=0
WQ Create Restart=0
WQ Fixed Restart=0
WQ System Summary=0
WQ Use Fixed Temperature=0
Sorting and Armoring Iterations= 10
XS Update Threshold= 0.02
Hydraulics Update Threshold= 0.02
Energy Slope Method= 1
Volume Change Method= 0
XS Weighting Method= 0
Number of US Weighted Cross Sections= 1
Number of DS Weighted Cross Sections= 1
Upstream XS Weight=0.25
Main XS Weight=0.5
Downstream XS Weight=0.25
Number of DS XS's Weighted with US Boundary= 1
Upstream Boundary Weight= 1
Weight of XSs Associated with US Boundary= 0
Number of US XS's Weighted with DS Boundary= 1
Downstream Boundary Weight= 0.5
Weight of XSs Associated with DS Boundary= 0.5
Sediment Output Level= 4
Mass or Volume Output= 0
Output Increment Type= 1
Profile and TS Output Increment= 10
XS Output Flag= 0
XS Output Increment= 10
Disregard all LS=0
Disregard all Conn=0
Disregard all Breaches=0
Disregard all Pumps=0

--- Elm 01 52.f01 (steady flow) ---

Flow Title=Multiple
Number of Profiles=7
Profile Names=10-year,25-year,50-year,1pct_min,100-year,1pct_plu,500-year
River Rch & RM= Elm 01 52,Reach-1,2814
      58      73      85      61      98     135     132
Boundary for River Rch & Prof#=Elm 01 52,Reach-1,1
Up Type=0
Dn Type=3
Dn Slope=0.005
Boundary for River Rch & Prof#=Elm 01 52,Reach-1,2
Up Type=0
Dn Type=3
Dn Slope=0.005
Boundary for River Rch & Prof#=Elm 01 52,Reach-1,3
Up Type=0
Dn Type=3
Dn Slope=0.005
Boundary for River Rch & Prof#=Elm 01 52,Reach-1,4
Up Type=0
Dn Type=3
Dn Slope=0.005
Boundary for River Rch & Prof#=Elm 01 52,Reach-1,5
Up Type=0
Dn Type=3
Dn Slope=0.005
Boundary for River Rch & Prof#=Elm 01 52,Reach-1,6
Up Type=0
Dn Type=3
Dn Slope=0.005
Boundary for River Rch & Prof#=Elm 01 52,Reach-1,7
Up Type=0
Dn Type=3
Dn Slope=0.005

--- Elm 01 52.g01 (geometry) ---

Geom Title=Existing Conditions
Program Version=4.10

River Reach=Elm 01 52       ,Reach-1
Reach XY= 30
        1565055.        6864738.      1565151.34      6864586.42
      1565154.07      6864498.48      1565010.47      6864340.45
      1564994.65      6864177.88      1564957.57      6864143.74
      1564895.31      6864127.22      1564808.12      6864036.38
      1564808.34      6863989.75      1564854.46      6863922.79
      1564855.45      6863677.81      1564851.22      6863639.56
      1564807.17      6863582.02       1564806.1      6863498.55
      1564852.73      6863432.06      1564856.23      6863298.51
      1564902.64      6863232.02      1564910.54      6863135.58
      1564996.81      6863044.02      1565027.87      6862964.17
      1565146.98      6862894.34      1565202.67      6862782.03
      1565208.62       6862689.5      1565296.82      6862594.04
      1565315.77       6862528.3       1565395.3      6862448.77
      1565461.06      6862429.85      1565525.35      6862368.22
      1565551.73      6862336.66        1565555.        6862288.

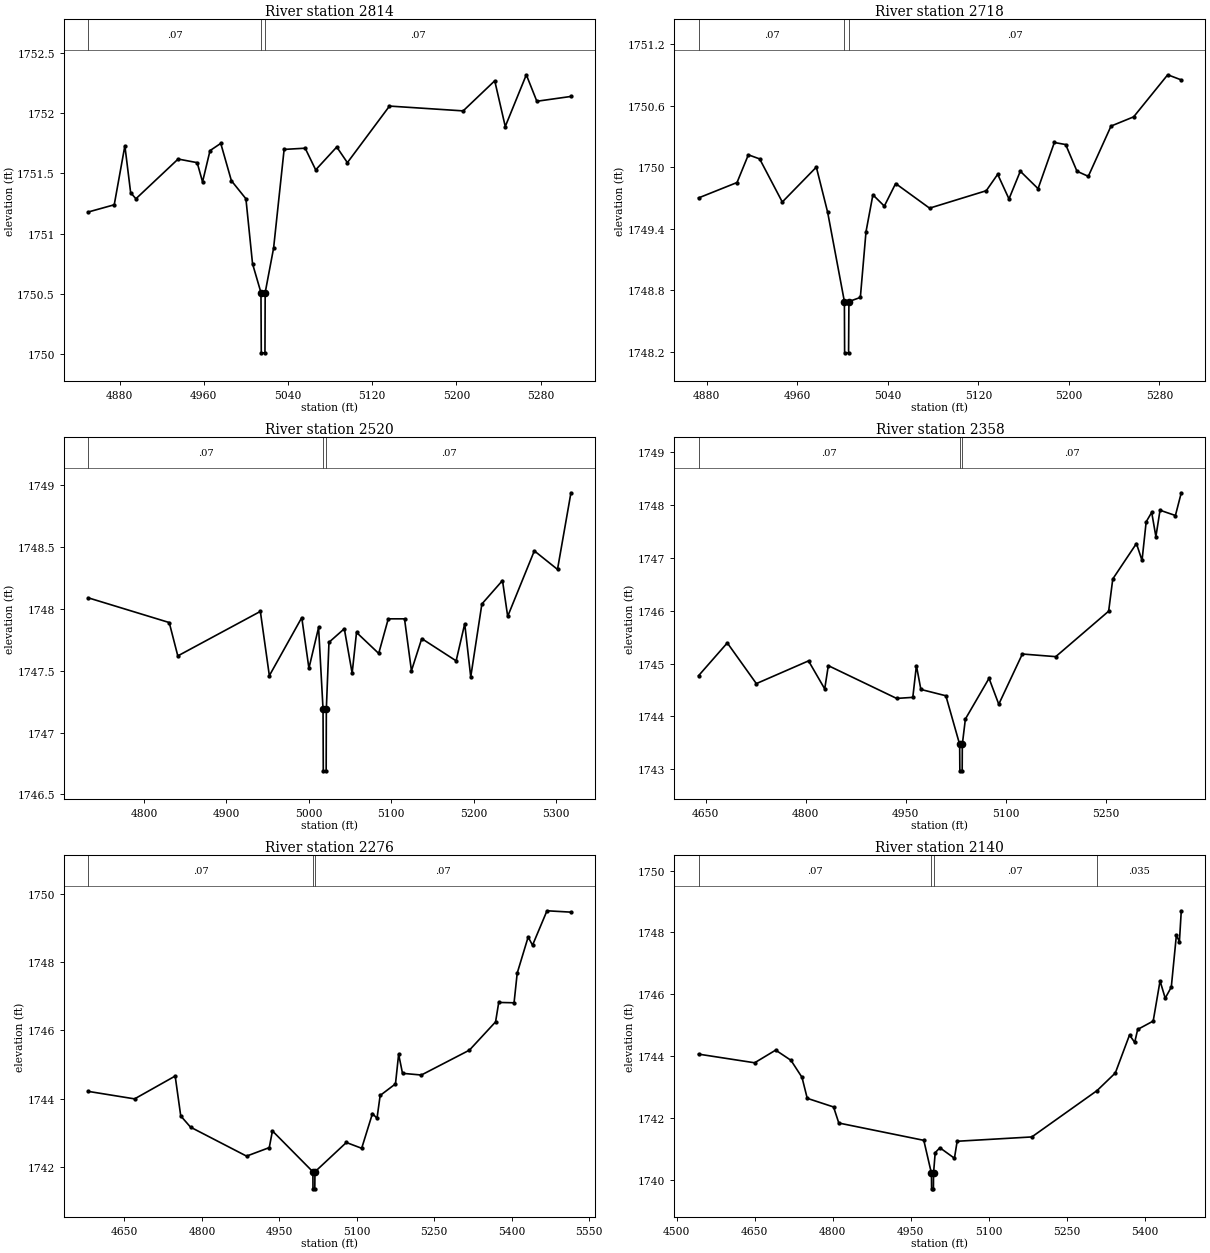
Type RM Length L Ch R = 1 ,2814    ,96,96,96
BEGIN DESCRIPTION:
Elm 01 52 2813.561
END DESCRIPTION:
XS GIS Cut Line= 3
       1565299.4      6864609.17      1565151.34      6864586.42
      1564842.57      6864591.04
#Sta/Elev= 30
  4850.2 1751.18  4874.9 1751.24    4885 1751.73  4890.5 1751.34  4895.5 1751.29
  4935.6 1751.62  4953.7 1751.59  4958.8 1751.43  4965.9 1751.69  4976.1 1751.75
  4986.2 1751.44    5000 1751.29  5006.3 1750.75  5014.3 1750.51  5014.6 1750.01
  5018.1 1750.01  5018.3 1750.51  5026.3 1750.88  5036.3  1751.7  5056.3 1751.71
  5066.3 1751.53  5086.3 1751.72  5096.4 1751.59  5136.4 1752.06  5206.4 1752.02
  5236.4 1752.27  5246.4 1751.89  5266.4 1752.32  5276.4  1752.1  5308.8 1752.14
#Mann= 3 ,-1 , 0
  4850.2     .07       0  5014.3     .07       0  5018.3     .07       0
Bank Sta=5014.3,5018.3
XS Rating Curve= 0 ,0
Exp/Cntr=0.3,0.1

Type RM Length L Ch R = 1 ,2718    ,198,198,198
BEGIN DESCRIPTION:
Elm 01 52 2718.42
END DESCRIPTION:
XS GIS Cut Line= 3
      1565278.98      6864486.79      1565146.38      6864492.08
        1564853.      6864511.18
#Sta/Elev= 30
  4872.7  1749.7  4906.7 1749.85  4916.7 1750.12  4926.7 1750.08  4946.7 1749.66
  4976.8    1750  4986.8 1749.56  5001.6 1748.69  5001.8 1748.19  5005.3 1748.19
  5005.6 1748.69  5015.7 1748.73  5020.7 1749.37  5026.8 1749.73  5036.9 1749.62
  5046.9 1749.84  5076.9  1749.6    5127 1749.77  5137.1 1749.93  5147.1 1749.69
  5157.1 1749.96  5172.8 1749.79  5187.2 1750.24  5197.2 1750.22  5207.2 1749.96
  5217.2 1749.91  5237.3  1750.4  5257.3 1750.49  5287.4  1750.9  5299.4 1750.85
#Mann= 3 ,-1 , 0
  4872.7     .07       0  5001.6     .07       0  5005.6     .07       0
Bank Sta=5001.6,5005.6
XS Rating Curve= 0 ,0
Exp/Cntr=0.3,0.1

Type RM Length L Ch R = 1 ,2520    ,162,162,162
BEGIN DESCRIPTION:
Elm 01 52 2520.14
END DESCRIPTION:
XS GIS Cut Line= 3
      1565282.84       6864323.7       1565012.7      6864347.99
      1564711.43      6864436.74
#Sta/Elev= 30
  4732.5 1748.09  4830.7 1747.89  4841.1 1747.62  4941.2 1747.98  4952.1 1747.46
  4991.4 1747.93  5000.1 1747.52  5011.8 1747.85  5017.2 1747.19  5017.5 1746.69
    5021 1746.69  5021.2 1747.19  5024.4 1747.73    5043 1747.84  5052.5 1747.48
  5057.8 1747.81  5084.7 1747.64  5096.3 1747.92    5116 1747.92  5124.4  1747.5
  5136.9 1747.76  5178.6 1747.58    5189 1747.88  5196.3 1747.45  5209.8 1748.04
  5234.8 1748.23  5241.1 1747.94  5273.4 1748.47  5301.5 1748.32  5317.8 1748.94
#Mann= 3 ,-1 , 0
  4732.5     .07       0  5017.2     .07       0  5021.2     .07       0
Bank Sta=5017.2,5021.2
XS Rating Curve= 0 ,0
Exp/Cntr=0.3,0.1

Type RM Length L Ch R = 1 ,2358    ,82,82,82
BEGIN DESCRIPTION:
Elm 01 52 2430.24
END DESCRIPTION:
XS GIS Cut Line= 3
      1565335.01       6864052.7      1565012.96      6864180.75
      1564709.34      6864405.63
#Sta/Elev= 30
  4639.2 1744.77  4682.3 1745.39  4725.9 1744.62  4804.2 1745.05  4828.5 1744.52
  4833.9 1744.96  4936.4 1744.34  4960.7 1744.36  4966.1 1744.96  4972.8 1744.51
  5010.3 1744.39    5031 1743.47  5031.3 1742.97  5034.8 1742.97    5035 1743.47
  5039.6 1743.95  5075.1 1744.72  5089.7 1744.23  5125.1 1745.18  5175.2 1745.13
  5254.6 1745.99  5260.8  1746.6  5296.3 1747.27  5304.7 1746.95  5310.9 1747.68
  5319.2 1747.86  5325.5  1747.4  5331.7  1747.9  5354.8  1747.8  5363.6 1748.23
#Mann= 3 ,-1 , 0
  4639.2     .07       0    5031     .07       0    5035     .07       0
Bank Sta=5031,5035
XS Rating Curve= 0 ,0
Exp/Cntr=0.3,0.1

Type RM Length L Ch R = 1 ,2276    ,136,136,136
BEGIN DESCRIPTION:
Elm 01 52 2308.83
END DESCRIPTION:
XS GIS Cut Line= 3
      1565321.75      6863969.51      1565010.67      6864091.59
      1564516.84      6864433.98
#Sta/Elev= 30
  4579.8 1744.21  4669.6 1743.99  4748.2 1744.66    4759 1743.49    4778 1743.16
  4886.5 1742.31  4930.5 1742.56  4936.6 1743.05    5015 1741.85  5015.2 1741.35
  5018.7 1741.35    5019 1741.85  5079.8 1742.71  5109.5 1742.54  5130.4 1743.56
  5139.2 1743.42  5145.3 1744.09    5175 1744.43  5181.1  1745.3  5188.6 1744.74
  5225.1 1744.69  5318.2 1745.42  5368.9 1746.25    5375 1746.82  5404.7 1746.81
  5410.8 1747.68    5432 1748.74  5440.5  1748.5  5468.5 1749.51  5514.9 1749.47
#Mann= 3 ,-1 , 0
  4579.8     .07       0    5015     .07       0    5019     .07       0
Bank Sta=5015,5019
XS Rating Curve= 0 ,0
Exp/Cntr=0.3,0.1

Type RM Length L Ch R = 1 ,2140    ,53,53,53
BEGIN DESCRIPTION:
Elm 01 52 20.0
END DESCRIPTION:
XS GIS Cut Line= 4
      1565281.53      6863985.71      1564952.21      6864035.76
      1564775.17      6864077.79      1564418.37      6864285.65
#Sta/Elev= 30
  4542.3 1744.06  4650.1 1743.78  4690.5 1744.19  4719.9 1743.86  4741.1 1743.31
  4751.2 1742.63  4801.8 1742.35  4811.9 1741.83  4975.3 1741.27    4990  1740.2
  4990.3  1739.7  4993.8  1739.7    4994  1740.2  4997.2 1740.87  5006.2 1741.03
  5034.2 1740.69  5039.4 1741.24    5183 1741.38  5308.4 1742.88  5343.5 1743.45
  5370.8 1744.68  5380.7 1744.44  5386.5 1744.86  5416.3 1745.13  5429.5 1746.43
  5439.4 1745.87  5451.1 1746.23  5460.9 1747.91  5466.7  1747.7  5470.3  1748.7
#Mann= 4 ,-1 , 0
  4542.3     .07       0    4990     .07       0    4994     .07       0
  5308.4    .035       0
Bank Sta=4990,4994
XS Rating Curve= 0 ,0
Exp/Cntr=0.3,0.1

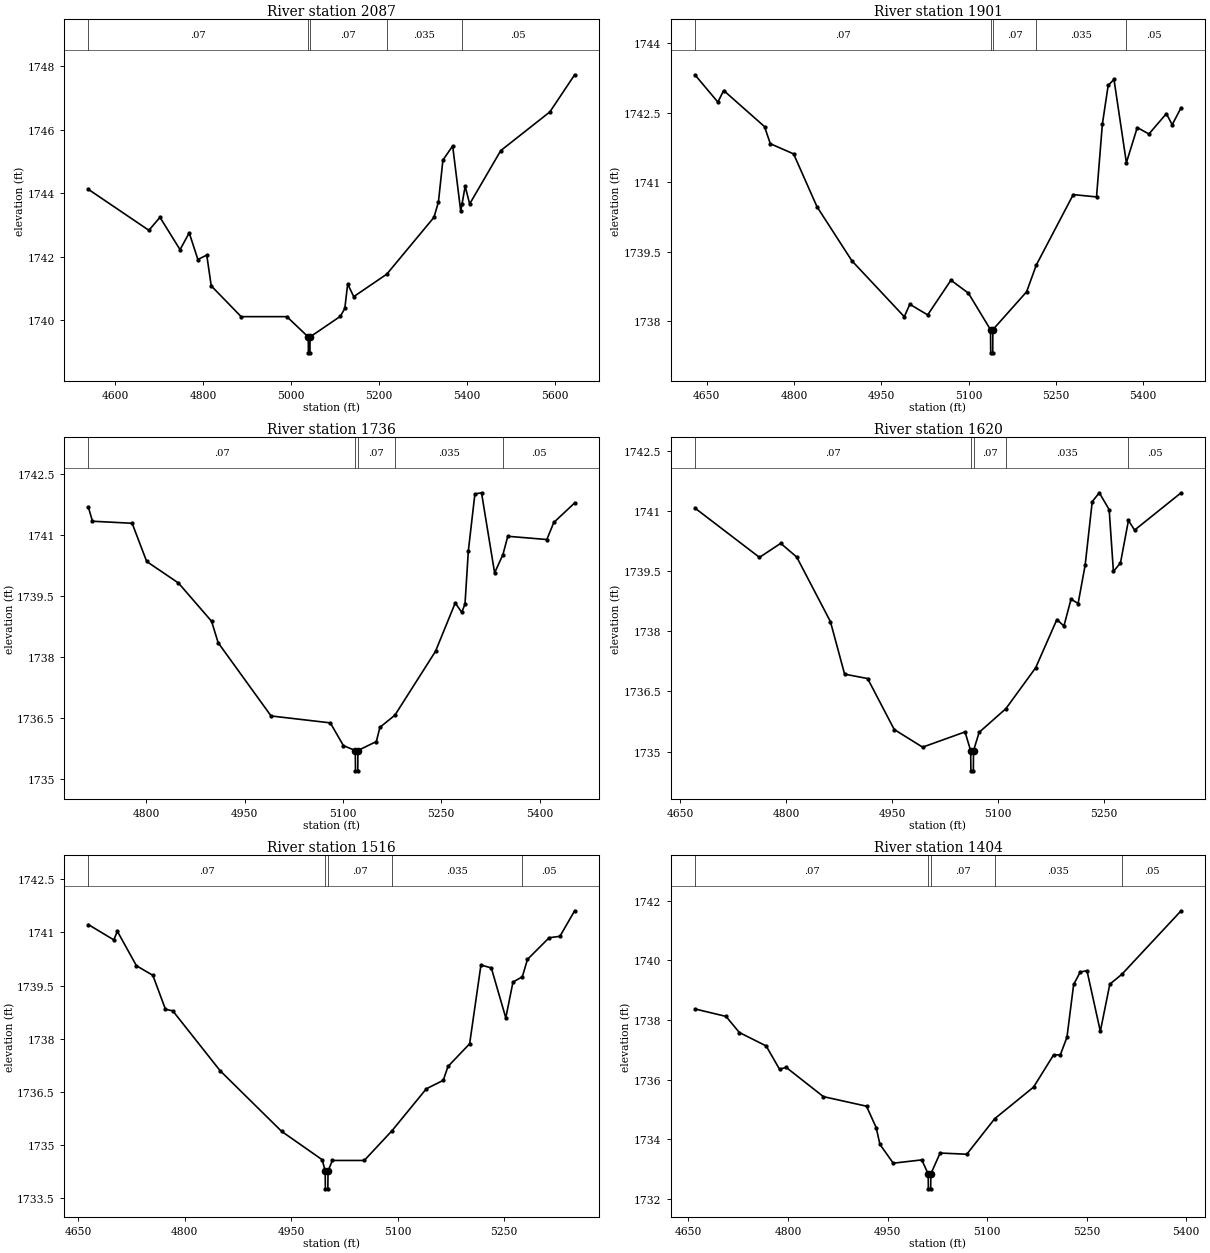
Type RM Length L Ch R = 1 ,2087    ,186,186,186
BEGIN DESCRIPTION:
Elm 01 52 2087.41
END DESCRIPTION:
XS GIS Cut Line= 3
      1565260.95      6863946.95      1564800.89       6864021.6
      1564169.46      6864130.89
#Sta/Elev= 30
  4538.8 1744.12  4676.5 1742.83  4701.7 1743.24  4747.4 1742.22  4768.3 1742.75
    4788 1741.91  4808.2 1742.05  4818.4 1741.08  4886.5 1740.11  4990.6 1740.11
  5039.3 1739.47  5039.6 1738.97  5043.1 1738.97  5043.3 1739.47  5112.3 1740.12
  5122.5 1740.37    5129 1741.14  5142.8 1740.74  5218.1 1741.45  5325.5 1743.24
  5335.6 1743.72  5345.8 1745.04    5368 1745.49  5386.4 1743.43  5389.5 1743.67
  5396.5 1744.22  5406.7 1743.66  5477.4 1745.34  5589.3 1746.56  5645.7 1747.73
#Mann= 5 ,-1 , 0
  4538.8     .07       0  5039.3     .07       0  5043.3     .07       0
  5218.1    .035       0  5389.5     .05       0
Bank Sta=5039.3,5043.3
XS Rating Curve= 0 ,0
Exp/Cntr=0.3,0.1

Type RM Length L Ch R = 1 ,1901    ,165,165,165
BEGIN DESCRIPTION:
Elm 01 52 1900.7
END DESCRIPTION:
XS GIS Cut Line= 3
      1565224.46      6863867.08      1564851.24      6863849.72
      1564389.72      6863837.58
#Sta/Elev= 30
  4629.9 1743.32  4669.4 1742.73  4679.4 1742.98  4749.5  1742.2  4759.5 1741.83
  4799.5 1741.61  4839.6 1740.47  4899.6  1739.3  4989.7 1738.09  4999.1 1738.36
  5029.8 1738.13  5069.8 1738.88  5099.8  1738.6  5137.8 1737.81  5138.1 1737.31
  5141.6 1737.31  5141.8 1737.81  5199.8 1738.63  5216.5 1739.21  5279.9 1740.73
  5319.9 1740.68  5329.9 1742.25  5339.9 1743.09  5349.9 1743.22  5371.2 1741.42
  5389.9 1742.18  5409.9 1742.04  5439.9 1742.48  5449.9 1742.24  5465.2 1742.61
#Mann= 5 ,-1 , 0
  4629.9     .07       0  5137.8     .07       0  5141.8     .07       0
  5216.5    .035       0  5371.2     .05       0
Bank Sta=5137.8,5141.8
XS Rating Curve= 0 ,0
Exp/Cntr=0.3,0.1

Type RM Length L Ch R = 1 ,1736    ,116,116,116
BEGIN DESCRIPTION:
Elm 01 52 1736.18
END DESCRIPTION:
XS GIS Cut Line= 3
      1565141.12      6863724.72      1564851.24      6863684.79
       1564403.3      6863650.07
#Sta/Elev= 30
  4711.6 1741.68  4717.8 1741.34  4778.3 1741.29  4800.5 1740.35    4849 1739.82
  4899.5 1738.88  4909.6 1738.35  4990.3 1736.55  5080.7 1736.38  5100.7 1735.82
  5118.8  1735.7  5119.1  1735.2  5122.6  1735.2  5122.8  1735.7  5150.9 1735.92
  5156.4 1736.27  5179.3 1736.57  5241.2 1738.14  5271.3 1739.33  5281.2  1739.1
  5286.2  1739.3  5291.3 1740.61  5301.3 1742.01  5311.4 1742.04  5331.4 1740.07
  5344.1 1740.52  5351.5 1740.97  5411.1 1740.89  5421.7 1741.31  5453.5 1741.79
#Mann= 5 ,-1 , 0
  4711.6     .07       0  5118.8     .07       0  5122.8     .07       0
  5179.3    .035       0  5344.1     .05       0
Bank Sta=5118.8,5122.8
XS Rating Curve= 0 ,0
Exp/Cntr=0.3,0.1

Type RM Length L Ch R = 1 ,1620    ,104,104,104
BEGIN DESCRIPTION:
Elm 01 52 1620.06
END DESCRIPTION:
XS GIS Cut Line= 3
      1565136.01      6863617.09       1564806.1       6863584.1
       1564449.2      6863568.51
#Sta/Elev= 30
  4670.8 1741.07  4762.3 1739.84  4792.4 1740.19    4815 1739.85  4862.8 1738.24
  4882.9 1736.93  4915.5 1736.82  4953.2 1735.55  4993.4 1735.11  5053.5 1735.49
  5061.5 1735.02  5061.8 1734.52  5065.3 1734.52  5065.5 1735.02  5073.5 1735.48
  5111.4 1736.07  5153.6 1737.09  5183.6 1738.29  5193.6 1738.13  5203.7  1738.8
  5213.7 1738.69  5223.7 1739.65  5233.7 1741.23  5243.7 1741.45  5257.7 1741.03
  5263.7 1739.49  5273.7  1739.7    5285 1740.76  5293.7 1740.52  5359.6 1741.45
#Mann= 5 ,-1 , 0
  4670.8     .07       0  5061.5     .07       0  5065.5     .07       0
  5111.4    .035       0    5285     .05       0
Bank Sta=5061.5,5065.5
XS Rating Curve= 0 ,0
Exp/Cntr=0.3,0.1

Type RM Length L Ch R = 1 ,1516    ,112,112,112
BEGIN DESCRIPTION:
Elm 01 52 1516.28
END DESCRIPTION:
XS GIS Cut Line= 3
      1565141.19      6863551.12      1564818.26       6863483.4
      1564469.67      6863419.24
#Sta/Elev= 30
  4664.6 1741.22  4700.3 1740.79  4705.4 1741.03  4732.2 1740.06  4755.3 1739.79
  4773.1 1738.83  4783.3 1738.79    4850  1737.1  4936.6 1735.39  4993.7 1734.59
  4997.9 1734.27  4998.1 1733.77  5001.6 1733.77  5001.9 1734.27    5008 1734.57
  5052.9 1734.57    5092 1735.41  5140.2 1736.59  5164.1 1736.83  5170.7 1737.22
  5201.2 1737.86  5217.1 1740.08  5231.7    1740  5252.1 1738.59  5262.2  1739.6
  5275.4 1739.75  5282.6 1740.24  5313.1 1740.85  5328.3 1740.89    5349 1741.61
#Mann= 5 ,-1 , 0
  4664.6     .07       0  4997.9     .07       0  5001.9     .07       0
    5092    .035       0  5275.4     .05       0
Bank Sta=4997.9,5001.9
XS Rating Curve= 0 ,0
Exp/Cntr=0.3,0.1

Type RM Length L Ch R = 1 ,1404    ,100,100,100
BEGIN DESCRIPTION:
Elm 01 52 1404
END DESCRIPTION:
XS GIS Cut Line= 3
      1565191.49      6863427.84      1564854.71      6863384.45
      1564464.08      6863341.04
#Sta/Elev= 30
  4659.7 1738.37  4706.6 1738.12  4726.7 1737.58  4767.1 1737.13  4787.2 1736.35
  4797.3 1736.41  4853.4 1735.43  4918.3 1735.11  4932.9 1734.39  4938.5 1733.83
  4958.6  1733.2  5001.6 1733.31  5011.2 1732.84  5011.5 1732.34    5015 1732.34
  5015.2 1732.84  5029.2 1733.54  5069.4  1733.5  5111.4 1734.69    5170 1735.75
  5200.2 1736.83  5210.3 1736.83  5220.3 1737.42  5230.4 1739.19  5240.4 1739.61
  5250.5 1739.65  5270.6 1737.62  5284.9  1739.2    5303 1739.53  5392.3 1741.66
#Mann= 5 ,-1 , 0
  4659.7     .07       0  5011.2     .07       0  5015.2     .07       0
  5111.4    .035       0    5303     .05       0
Bank Sta=5011.2,5015.2
XS Rating Curve= 0 ,0
Exp/Cntr=0.3,0.1

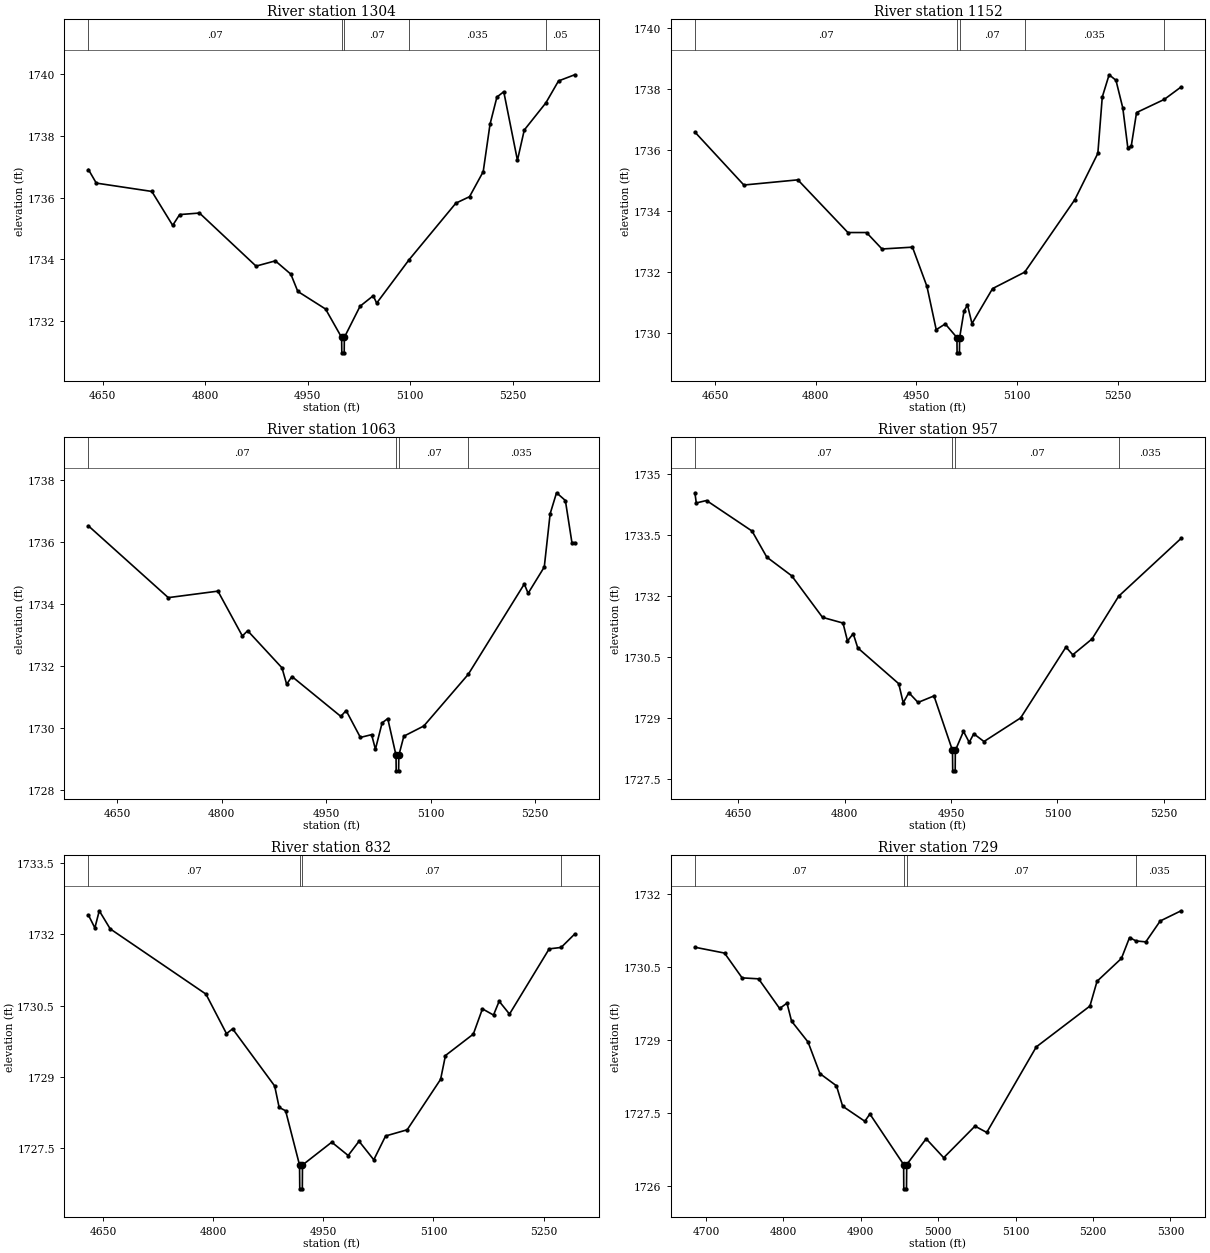
Type RM Length L Ch R = 1 ,1304    ,152,152,152
BEGIN DESCRIPTION:
Elm 01 52 1304.33
END DESCRIPTION:
XS GIS Cut Line= 3
      1565226.26       6863353.2      1564859.92      6863285.49
      1564521.41      6863268.13
#Sta/Elev= 30
  4629.1 1736.91  4640.6 1736.47  4721.9  1736.2  4752.4  1735.1  4762.6 1735.45
  4791.6  1735.5  4874.4 1733.78  4902.6 1733.95  4925.3 1733.52  4935.5 1732.96
  4976.1 1732.39  4999.6 1731.47  4999.9 1730.97  5003.4 1730.97  5003.6 1731.47
  5026.6 1732.48  5045.9 1732.82  5050.9 1732.58  5098.1 1733.98  5166.8 1735.82
  5186.8 1736.03  5206.8 1736.84  5216.8 1738.38  5226.9 1739.26  5236.9 1739.43
  5256.9 1737.21  5266.9 1738.19  5298.5 1739.07    5317 1739.78  5340.6 1739.98
#Mann= 5 ,-1 , 0
  4629.1     .07       0  4999.6     .07       0  5003.6     .07       0
  5098.1    .035       0  5298.5     .05       0
Bank Sta=4999.6,5003.6
XS Rating Curve= 0 ,0
Exp/Cntr=0.3,0.1

Type RM Length L Ch R = 1 ,1152    ,89,89,89
BEGIN DESCRIPTION:
Elm 01 52 1151.89
END DESCRIPTION:
XS GIS Cut Line= 3
      1565236.62      6863337.55      1564908.53      6863148.33
      1564569.97      6863077.15
#Sta/Elev= 30
  4619.7  1736.6  4692.7 1734.86  4773.2 1735.03  4847.8  1733.3  4875.5  1733.3
  4898.6 1732.76    4944 1732.82  4965.6 1731.53  4979.4 1730.11  4992.9  1730.3
  5010.3 1729.85  5010.5 1729.35    5014 1729.35  5014.3 1729.85  5020.9 1730.73
    5026 1730.92  5032.7 1730.31  5063.4 1731.46  5111.3    1732    5186 1734.38
  5220.3  1735.9  5226.9 1737.75  5237.1 1738.48  5247.3  1738.3  5257.5 1737.39
    5265 1736.08  5270.1 1736.14    5278 1737.24  5319.2 1737.67  5344.4 1738.08
#Mann= 5 ,-1 , 0
  4619.7     .07       0  5010.3     .07       0  5014.3     .07       0
  5111.3    .035       0  5319.2    .045       0
Bank Sta=5010.3,5014.3
XS Rating Curve= 0 ,0
Exp/Cntr=0.3,0.1

Type RM Length L Ch R = 1 ,1063    ,106,106,106
BEGIN DESCRIPTION:
Elm 01 52 1063.27
END DESCRIPTION:
XS GIS Cut Line= 3
      1565257.47      6863337.55      1564960.62      6863078.89
      1564682.87      6862953.91
#Sta/Elev= 30
  4608.7 1736.53  4723.4 1734.21  4794.7 1734.42  4829.8 1732.97  4837.4 1733.14
  4886.7 1731.94  4893.4 1731.41    4901 1731.66  4971.2 1730.37  4978.8 1730.56
  4999.3 1729.69  5015.4 1729.78  5020.9 1729.31  5030.5 1730.16  5038.6  1730.3
  5050.5 1729.11  5050.7 1728.61  5054.2 1728.61  5054.5 1729.11  5061.7 1729.73
  5090.4 1730.06  5154.2 1731.73  5234.7 1734.65  5240.2 1734.35  5263.4  1735.2
  5271.8 1736.92    5281  1737.6  5293.7 1737.35  5303.1 1735.99    5307 1735.99
#Mann= 4 ,-1 , 0
  4608.7     .07       0  5050.5     .07       0  5054.5     .07       0
  5154.2    .035       0
Bank Sta=5050.5,5054.5
XS Rating Curve= 0 ,0
Exp/Cntr=0.3,0.1

Type RM Length L Ch R = 1 ,957     ,125,125,125
BEGIN DESCRIPTION:
Elm 01 52 956.84
END DESCRIPTION:
XS GIS Cut Line= 3
      1565332.11      6863243.79      1565008.89      6862989.43
      1564774.82      6862846.23
#Sta/Elev= 30
  4588.7 1734.53  4590.7 1734.28  4605.1 1734.34  4669.3 1733.59  4690.1 1732.95
  4725.3 1732.49  4768.7 1731.47  4797.6 1731.33  4803.9 1730.89    4812 1731.07
  4818.4 1730.72  4876.2 1729.84  4882.5 1729.37  4890.4 1729.62  4903.4 1729.38
  4925.9 1729.54    4952  1728.2  4952.3  1727.7  4955.8  1727.7    4956  1728.2
  4967.5 1728.67  4975.6  1728.4    4982 1728.61  4996.4 1728.42  5048.1    1729
    5112 1730.74  5121.6 1730.55  5148.8 1730.94  5186.4 1731.99  5274.4 1733.41
#Mann= 4 ,-1 , 0
  4588.7     .07       0    4952     .07       0    4956     .07       0
  5186.4    .035       0
Bank Sta=4952,4956
XS Rating Curve= 0 ,0
Exp/Cntr=0.3,0.1

Type RM Length L Ch R = 1 ,832     ,103,103,103
BEGIN DESCRIPTION:
Elm 01 52 832.21
END DESCRIPTION:
XS GIS Cut Line= 3
      1565417.25      6863137.94      1565115.13      6862931.32
      1564854.72      6862788.96
#Sta/Elev= 30
  4629.6  1732.4  4638.4 1732.13  4644.4 1732.49  4659.3 1732.11  4789.8 1730.74
  4817.8 1729.91  4826.2 1730.01  4883.5 1728.81  4889.6 1728.36  4898.4 1728.29
  4917.4 1727.15  4917.7 1726.65  4921.2 1726.65  4921.4 1727.15  4961.3 1727.63
  4983.7 1727.35  4998.5 1727.65  5018.6 1727.26  5034.7 1727.76  5064.1 1727.89
  5109.7 1728.95  5116.3 1729.45  5154.3  1729.9  5166.7 1730.43  5181.8  1730.3
  5189.5 1730.59  5203.6 1730.32  5257.7 1731.69    5274 1731.72  5292.4    1732
#Mann= 4 ,-1 , 0
  4629.6     .07       0  4917.4     .07       0  4921.4     .07       0
    5274    .035       0
Bank Sta=4917.4,4921.4
XS Rating Curve= 0 ,0
Exp/Cntr=0.3,0.1

Type RM Length L Ch R = 1 ,729     ,72,72,72
BEGIN DESCRIPTION:
Elm 01 52 728.79
END DESCRIPTION:
XS GIS Cut Line= 3
       1565427.6      6863007.69       1565156.8      6862841.04
      1564861.63      6862745.55
#Sta/Elev= 30
  4685.6 1730.91  4723.9 1730.79  4746.6 1730.28  4767.9 1730.26  4795.1 1729.65
  4804.6 1729.76  4810.5 1729.39  4831.8 1728.96  4847.2 1728.31  4868.5 1728.06
  4876.5 1727.64  4905.2 1727.33  4911.7 1727.48  4955.3 1726.44  4955.5 1725.94
    4959 1725.94  4959.3 1726.44  4984.4 1726.97  5007.1 1726.58  5047.5 1727.23
  5062.7  1727.1  5126.7 1728.86    5196  1729.7  5205.2 1730.21  5236.7 1730.68
  5247.2 1731.11  5255.5 1731.04  5268.2 1731.02  5286.8 1731.45  5313.8 1731.66
#Mann= 4 ,-1 , 0
  4685.6     .07       0  4955.3     .07       0  4959.3     .07       0
  5255.5    .035       0
Bank Sta=4955.3,4959.3
XS Rating Curve= 0 ,0
Exp/Cntr=0.3,0.1

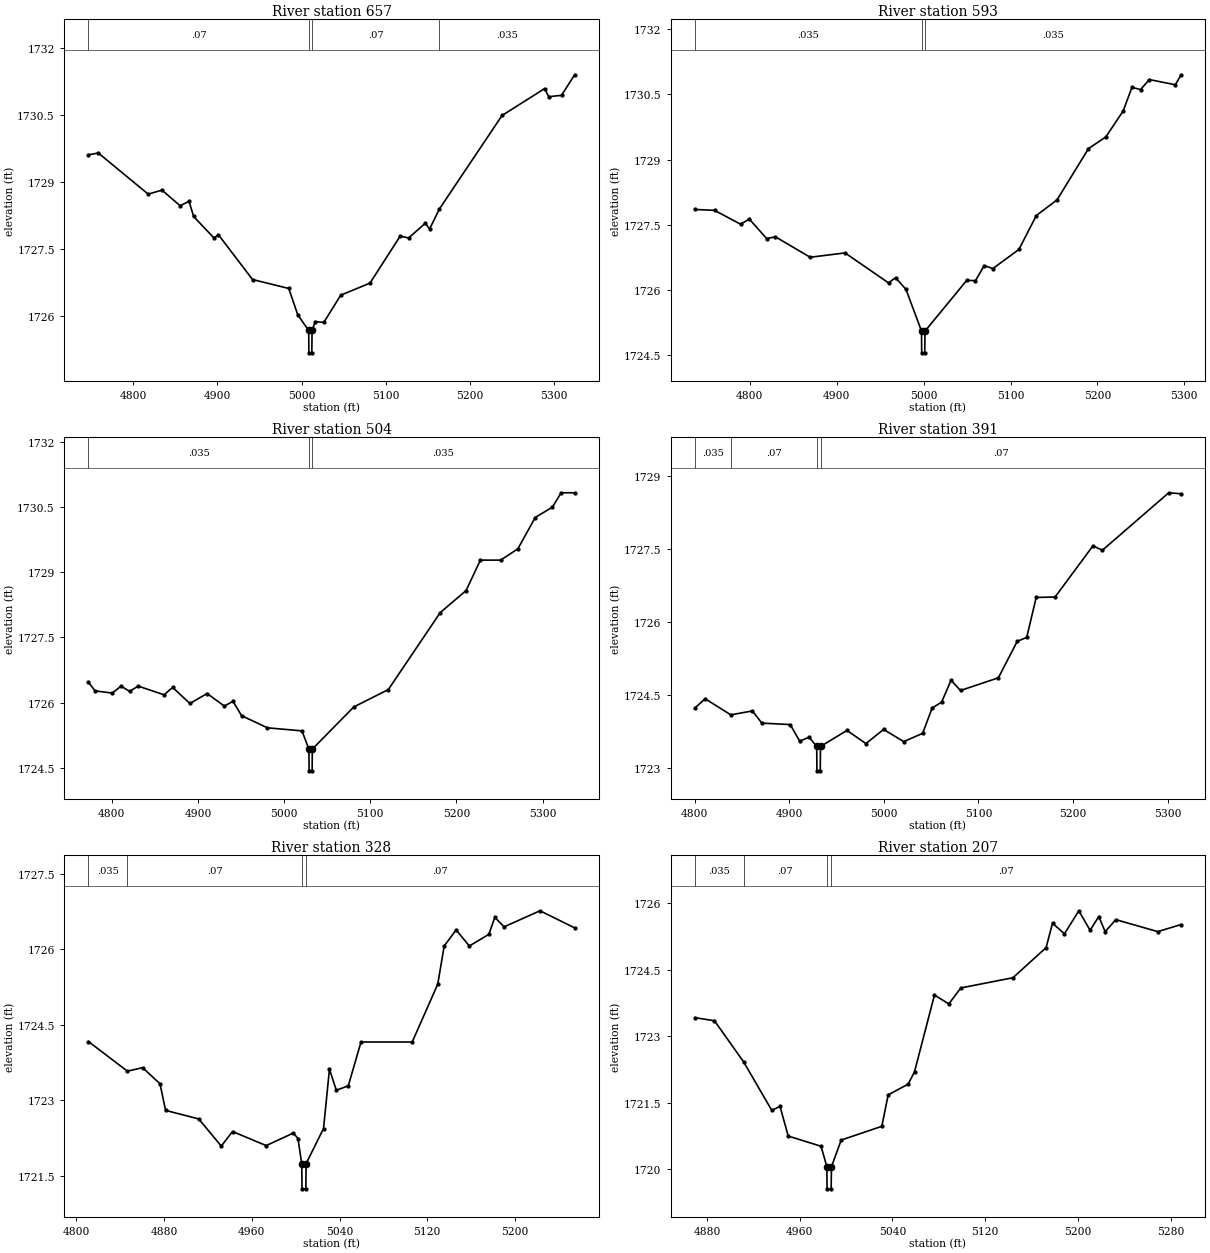
Type RM Length L Ch R = 1 ,657     ,64,64,64
BEGIN DESCRIPTION:
Elm 01 52 657.16
END DESCRIPTION:
XS GIS Cut Line= 3
      1565436.33      6862879.24      1565196.73      6862783.75
      1564879.54      6862738.69
#Sta/Elev= 30
  4746.5  1729.6  4758.3 1729.64  4817.6 1728.72    4834 1728.81  4855.6 1728.46
  4866.2 1728.56  4871.6 1728.22  4895.8 1727.74  4901.2 1727.81  4941.7 1726.81
  4984.8 1726.61  4995.5 1726.02  5008.5 1725.67  5008.7 1725.17  5012.2 1725.17
  5012.5 1725.67  5016.3 1725.87  5026.4 1725.85  5046.6 1726.46  5081.4 1726.73
  5117.3 1727.78  5127.4 1727.74  5147.2 1728.07  5152.3 1727.94    5164 1728.39
  5238.5 1730.48    5289 1731.08  5294.1  1730.9  5309.2 1730.93  5324.8 1731.39
#Mann= 4 ,-1 , 0
  4746.5     .07       0  5008.5     .07       0  5012.5     .07       0
    5164    .035       0
Bank Sta=5008.5,5012.5
XS Rating Curve= 0 ,0
Exp/Cntr=0.3,0.1

Type RM Length L Ch R = 1 ,593     ,89,89,89
BEGIN DESCRIPTION:
Elm 01 52 592.75
END DESCRIPTION:
XS GIS Cut Line= 3
      1565467.53      6862735.14       1565200.2      6862721.25
      1564908.41       6862724.7
#Sta/Elev= 30
  4736.8 1727.85  4759.4 1727.83  4789.4 1727.51  4799.4 1727.63  4819.4 1727.18
  4829.5 1727.22  4869.5 1726.75  4909.6 1726.85  4959.6 1726.16  4967.7 1726.28
  4979.7 1726.01  4997.6 1725.05  4997.8 1724.55  5001.3 1724.55  5001.6 1725.05
  5049.7 1726.22  5059.7 1726.21  5069.7 1726.56  5079.7 1726.49  5109.7 1726.93
  5129.7 1727.71  5153.5 1728.07  5189.7 1729.25  5209.7 1729.52  5229.7 1730.12
  5239.7 1730.66  5249.7 1730.61  5259.7 1730.84  5289.7 1730.72  5296.3 1730.95
#Mann= 3 ,-1 , 0
  4736.8    .035       0  4997.6    .035       0  5001.6    .035       0
Bank Sta=4997.6,5001.6
XS Rating Curve= 0 ,0
Exp/Cntr=0.3,0.1

Type RM Length L Ch R = 1 ,504     ,113,113,113
BEGIN DESCRIPTION:
Elm 01 52 503.54
END DESCRIPTION:
XS GIS Cut Line= 3
      1565472.77      6862641.39      1565241.87       6862646.6
      1564909.31      6862670.85
#Sta/Elev= 30
  4772.8 1726.47  4780.6 1726.27  4800.6 1726.22  4810.6 1726.38  4820.6 1726.26
  4830.6 1726.38  4860.6 1726.18  4870.6 1726.35  4890.6 1725.98  4910.6 1726.21
  4930.6 1725.92  4940.6 1726.03  4950.6  1725.7  4980.6 1725.42  5020.7 1725.35
  5028.7 1724.93    5029 1724.43  5032.5 1724.43  5032.7 1724.93  5080.8  1725.9
  5120.9  1726.3  5181.1 1728.07  5211.2 1728.58  5227.8 1729.28  5251.3 1729.28
  5271.3 1729.54  5291.4 1730.26  5311.4  1730.5  5321.5 1730.83  5337.2 1730.83
#Mann= 3 ,-1 , 0
  4772.8    .035       0  5028.7    .035       0  5032.7    .035       0
Bank Sta=5028.7,5032.7
XS Rating Curve= 0 ,0
Exp/Cntr=0.3,0.1

Type RM Length L Ch R = 1 ,391     ,63,63,63
BEGIN DESCRIPTION:
Elm 01 52 391.18
END DESCRIPTION:
XS GIS Cut Line= 3
      1565505.75      6862561.53      1565302.63      6862556.32
      1564991.86      6862551.11
#Sta/Elev= 30
  4800.2 1724.24    4811 1724.43  4838.2  1724.1    4861 1724.18    4871 1723.93
    4901  1723.9    4911 1723.56    4921 1723.64    4929 1723.45  4929.2 1722.95
  4932.7 1722.95    4933 1723.45    4961 1723.78    4981 1723.51  4999.7  1723.8
    5021 1723.55    5041 1723.72    5051 1724.24    5061 1724.36    5071 1724.81
    5081  1724.6    5121 1724.86    5141 1725.61    5151 1725.69    5161 1726.51
    5181 1726.52    5221 1727.57    5231 1727.48  5301.1 1728.66  5314.2 1728.64
#Mann= 4 ,-1 , 0
  4800.2    .035       0  4838.2     .07       0    4929     .07       0
    4933     .07       0
Bank Sta=4929,4933
XS Rating Curve= 0 ,0
Exp/Cntr=0.3,0.1

Type RM Length L Ch R = 1 ,328     ,121,121,121
BEGIN DESCRIPTION:
Elm 01 52 328.2
END DESCRIPTION:
XS GIS Cut Line= 3
      1565523.15      6862547.65      1565340.83      6862505.97
      1565106.09      6862402.41
#Sta/Elev= 30
  4810.9 1724.17  4846.5 1723.58  4860.3 1723.65  4876.2 1723.33  4881.3  1722.8
  4911.6 1722.63  4932.1 1722.09  4942.4 1722.38  4973.1  1722.1  4997.9 1722.35
  5002.1 1722.24  5005.5 1721.74  5005.8 1721.24  5009.3 1721.24  5009.5 1721.74
  5025.4 1722.44  5030.8 1723.62  5037.1  1723.2    5048 1723.29  5059.6 1724.16
  5106.3 1724.16  5129.6 1725.31  5135.5 1726.07  5146.4 1726.39  5158.4 1726.07
  5176.2  1726.3  5181.7 1726.64  5190.1 1726.45  5222.9 1726.77  5254.5 1726.43
#Mann= 4 ,-1 , 0
  4810.9    .035       0  4846.5     .07       0  5005.5     .07       0
  5009.5     .07       0
Bank Sta=5005.5,5009.5
XS Rating Curve= 0 ,0
Exp/Cntr=0.3,0.1

Type RM Length L Ch R = 1 ,207     ,137,137,137
BEGIN DESCRIPTION:
Elm 01 52 206.64
END DESCRIPTION:
XS GIS Cut Line= 3
      1565526.57      6862530.26      1565436.31      6862438.27
      1565174.16      6862313.27
#Sta/Elev= 30
  4869.6 1723.42  4886.5 1723.35  4911.7 1722.42  4935.9 1721.33    4943 1721.42
  4950.1 1720.75  4978.4 1720.52  4983.4 1720.06  4983.6 1719.56  4987.1 1719.56
  4987.4 1720.06  4995.8 1720.66  5030.8 1720.97  5036.3 1721.68  5053.5 1721.92
    5059  1722.2  5076.2 1723.93  5088.6 1723.73  5098.9 1724.09  5143.9 1724.32
  5172.5    1725    5178 1725.55  5188.3 1725.31  5200.7 1725.83  5210.4 1725.39
  5217.9  1725.7  5223.4 1725.36  5232.6 1725.63  5268.8 1725.36  5288.9 1725.52
#Mann= 4 ,-1 , 0
  4869.6    .035       0  4911.7     .07       0  4983.4     .07       0
  4987.4     .07       0
Bank Sta=4983.4,4987.4
XS Rating Curve= 0 ,0
Exp/Cntr=0.3,0.1

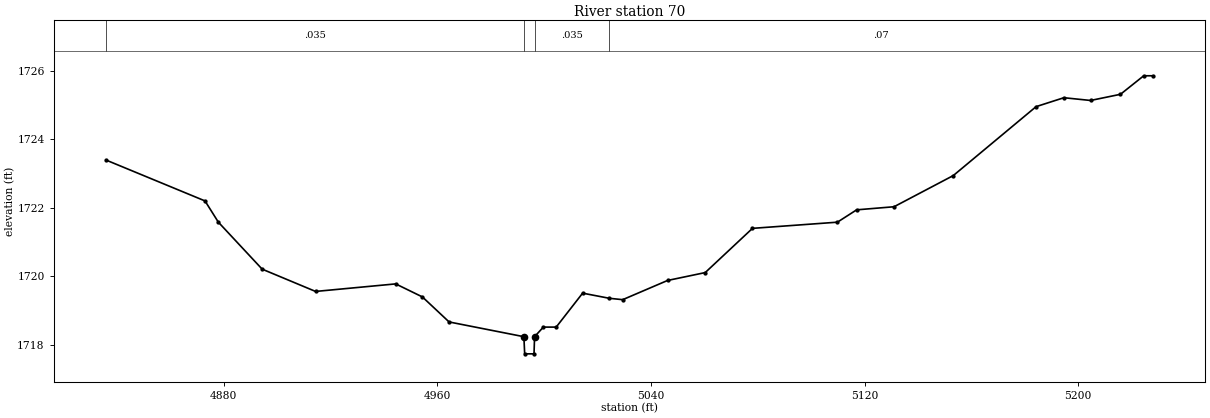
Type RM Length L Ch R = 1 ,70      ,0,0,0
BEGIN DESCRIPTION:
Elm 01 52 69.557
END DESCRIPTION:
XS GIS Cut Line= 3
      1565540.48      6862516.43      1565538.54      6862352.44
      1565323.46       6862276.8
#Sta/Elev= 30
    4836 1723.39    4873  1722.2    4878 1721.58  4894.4 1720.21  4914.4 1719.56
  4944.4 1719.78  4954.4  1719.4  4964.4 1718.67  4992.4 1718.24  4992.7 1717.74
  4996.2 1717.74  4996.4 1718.24  4999.7 1718.52  5004.5 1718.52  5014.4 1719.51
  5024.4 1719.36  5029.4 1719.32  5046.2 1719.88  5060.3 1720.11    5078  1721.4
  5109.8 1721.58    5117 1721.94    5131 1722.03  5153.2 1722.94  5184.2 1724.95
  5194.6 1725.21  5204.6 1725.13  5215.8 1725.31  5224.5 1725.85    5228 1725.85
#Mann= 4 ,-1 , 0
    4836    .035       0  4992.4     .07       0  4996.4    .035       0
  5024.4     .07       0
Bank Sta=4992.4,4996.4
XS Rating Curve= 0 ,0
Exp/Cntr=0.3,0.1

Chan Stop Cuts=-1
Use User Specified Reach Order=0
Composite Channel Slope=5