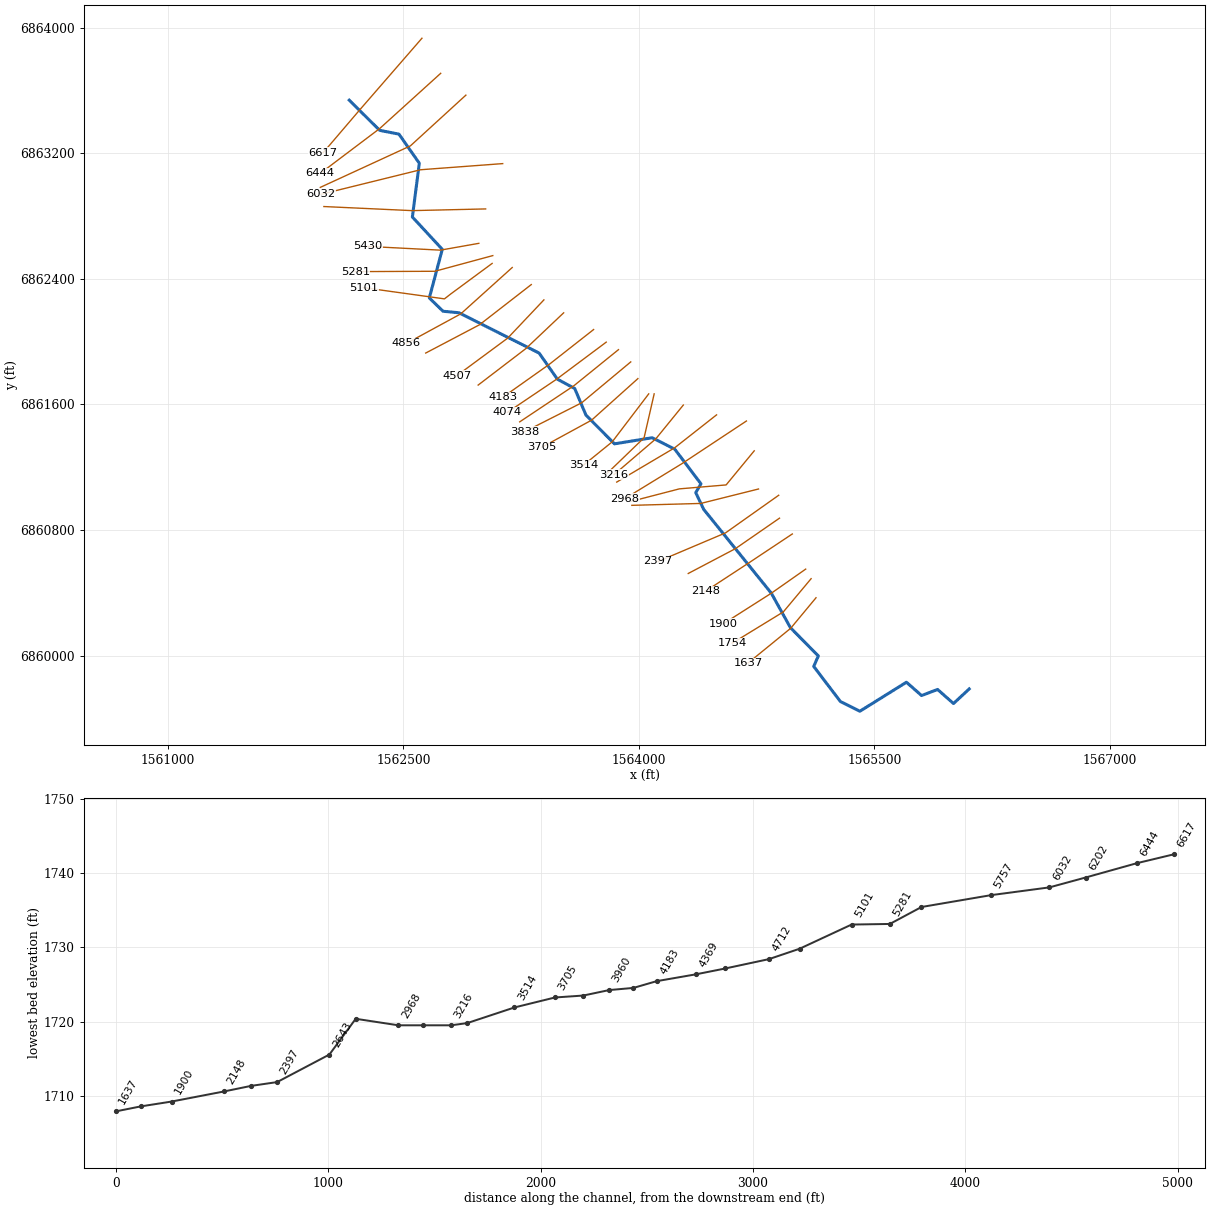
--- Elm 01 53.prj (project) ---

Proj Title=Elm 01 53 Base Level Engineering
Current Plan=p01
Default Exp/Contr=0.3,0.1
English Units
Geom File=g01
Flow File=f01
Plan File=p01
BEGIN DESCRIPTION:
Elm 01 53
END DESCRIPTION:

--- Elm 01 53.p01 (plan) ---

Plan Title=Multiple Run
Short Identifier=Multiple
Geom File=g01
Flow File=f01
Subcritical Flow
K Sum by GR= 0
Std Step Tol= 0.01
Critical Tol= 0.01
Num of Std Step Trials= 20
Max Error Tol= 0.3
Flow Tol Ratio= 0.001
Split Flow NTrial= 30
Split Flow Tol= 0.02
Split Flow Ratio= 0.02
Log Output Level= 0
Friction Slope Method= 1
Unsteady Friction Slope Method= 2
Unsteady Bridges Friction Slope Method= 1
Parabolic Critical Depth
Global Vel Dist=  1 , 1 , 1
Global Log Level= 0
CheckData=True
Encroach Param= -1, 0, 0, 0
BEGIN DESCRIPTION:
Multiple Run
END DESCRIPTION:

--- Elm 01 53.f01 (steady flow) ---

Flow Title=Multiple
Number of Profiles=7
Profile Names=10-year,25-year,50-year,1pct_min,100-year,1pct_plu,500-year
River Rch & RM= Elm 01 53,Reach-1,6617
     120     158     188     139     223     306     316
Boundary for River Rch & Prof#=Elm 01 53,Reach-1,1
Up Type=0
Dn Type=3
Dn Slope=0.005
Boundary for River Rch & Prof#=Elm 01 53,Reach-1,2
Up Type=0
Dn Type=3
Dn Slope=0.005
Boundary for River Rch & Prof#=Elm 01 53,Reach-1,3
Up Type=0
Dn Type=3
Dn Slope=0.005
Boundary for River Rch & Prof#=Elm 01 53,Reach-1,4
Up Type=0
Dn Type=3
Dn Slope=0.005
Boundary for River Rch & Prof#=Elm 01 53,Reach-1,5
Up Type=0
Dn Type=3
Dn Slope=0.005
Boundary for River Rch & Prof#=Elm 01 53,Reach-1,6
Up Type=0
Dn Type=3
Dn Slope=0.005
Boundary for River Rch & Prof#=Elm 01 53,Reach-1,7
Up Type=0
Dn Type=3
Dn Slope=0.005

--- Elm 01 53.g01 (geometry) ---

Geom Title=Existing Conditions

River Reach=Elm 01 53,Reach-1
Reach XY= 30
      1562155.00      6863538.00      1562348.83      6863345.86
      1562471.79      6863321.56      1562601.33      6863136.42
      1562557.06      6862793.85      1562747.68      6862588.10
      1562665.18      6862278.29      1562752.56      6862193.52
      1562853.41      6862184.17      1563364.70      6861927.24
      1563481.17      6861760.86      1563591.52      6861701.56
      1563663.14      6861531.94      1563844.94      6861349.10
      1564084.97      6861387.94      1564228.84      6861315.15
      1564395.70      6861094.67      1564362.78      6861038.09
      1564413.12      6860931.95      1564844.22      6860397.68
      1564965.78      6860178.32      1565143.76      6859998.00
      1565114.30      6859931.33      1565284.53      6859707.62
      1565408.31      6859646.02      1565705.09      6859830.69
      1565801.59      6859745.85      1565903.35      6859784.82
      1566005.00      6859694.98      1566105.00      6859788.00

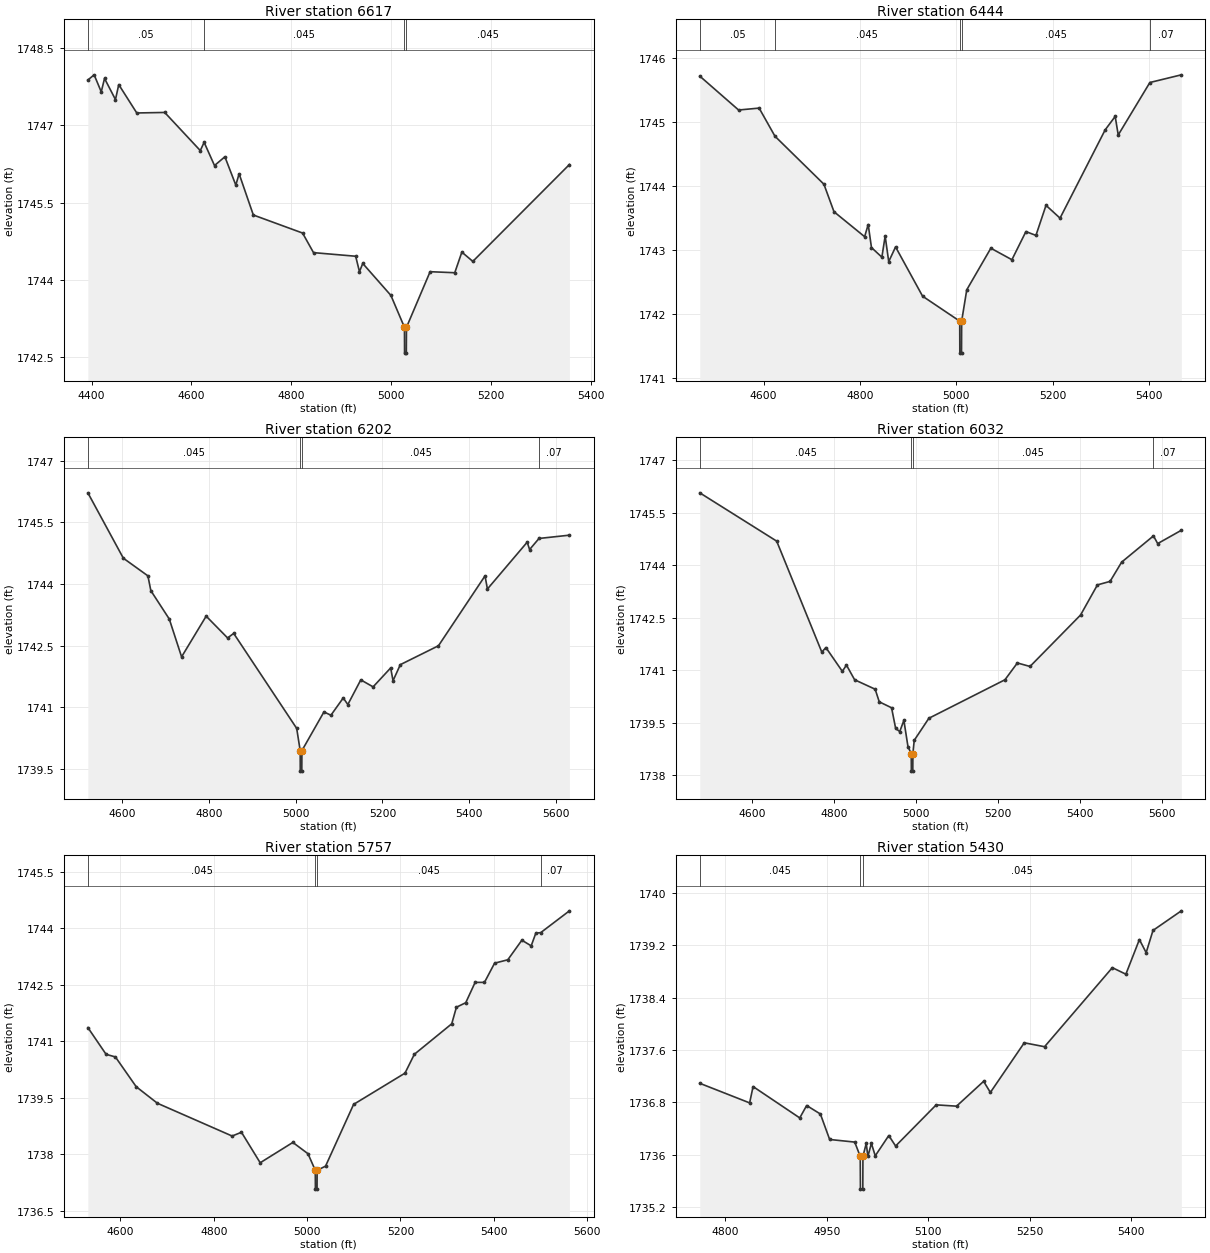
Type RM Length L Ch R = 1,6617,173,173,173
BEGIN DESCRIPTION:
Elm 01 53 6616.879
END DESCRIPTION:
XS GIS Cut Line= 3
      1562618.14      6863932.59      1562219.61      6863473.95
      1561987.39      6863202.14
#Sta/Elev= 30
  4392.4 1747.88  4405.0 1747.98  4419.2 1747.65  4425.8 1747.91  4447.7 1747.50
  4454.3 1747.79  4490.4 1747.24  4546.4 1747.25  4617.7 1746.51  4625.4 1746.67
  4646.2 1746.22  4667.0 1746.39  4688.9 1745.84  4695.5 1746.06  4724.0 1745.26
  4822.7 1744.91  4844.6 1744.53  4929.1 1744.46  4936.7 1744.16  4943.3 1744.32
  4999.7 1743.70  5026.9 1743.08  5027.1 1742.58  5030.6 1742.58  5030.9 1743.08
  5078.3 1744.16  5127.7 1744.14  5141.9 1744.54  5163.9 1744.36  5357.5 1746.24
#Mann=4,-1,0
  4392.4    0.05       0  4625.4   0.045       0  5026.9   0.045       0
  5030.9   0.045       0
Bank Sta=5026.9,5030.9
Exp/Cntr=0.3,0.1

Type RM Length L Ch R = 1,6444,242,242,242
BEGIN DESCRIPTION:
Elm 01 53 6444.2
END DESCRIPTION:
XS GIS Cut Line= 3
      1562737.55      6863709.12      1562349.07      6863357.54
      1561969.33      6863071.11
#Sta/Elev= 30
  4467.5 1745.72  4548.1 1745.19  4590.7 1745.22  4623.6 1744.78  4725.2 1744.03
  4746.1 1743.60  4809.7 1743.21  4817.1 1743.40  4823.9 1743.04  4845.5 1742.89
  4852.3 1743.22  4859.7 1742.82  4873.9 1743.05  4930.0 1742.28  5007.1 1741.89
  5007.3 1741.39  5010.8 1741.39  5011.1 1741.89  5021.7 1742.38  5071.7 1743.03
  5115.4 1742.85  5144.5 1743.29  5165.3 1743.23  5186.2 1743.70  5215.3 1743.50
  5309.0 1744.88  5329.8 1745.09  5336.1 1744.80  5401.8 1745.62  5467.1 1745.74
#Mann=5,-1,0
  4467.5    0.05       0  4623.6   0.045       0  5007.1   0.045       0
  5011.1   0.045       0  5401.8    0.07       0
Bank Sta=5007.1,5011.1
Exp/Cntr=0.3,0.1

Type RM Length L Ch R = 1,6202,170,170,170
BEGIN DESCRIPTION:
Elm 01 53 6202.22
END DESCRIPTION:
XS GIS Cut Line= 3
      1562898.11      6863570.20      1562544.38      6863246.86
      1561970.61      6862982.71
#Sta/Elev= 30
  4520.6 1746.22  4602.4 1744.63  4659.1 1744.20  4665.9 1743.84  4708.4 1743.15
  4736.8 1742.23  4793.5 1743.22  4842.9 1742.69  4857.0 1742.80  5002.3 1740.49
  5010.4 1739.95  5010.6 1739.45  5014.1 1739.45  5014.4 1739.95  5065.2 1740.89
  5081.3 1740.81  5109.7 1741.23  5120.3 1741.07  5150.2 1741.67  5178.6 1741.50
  5219.1 1741.96  5224.6 1741.65  5241.4 1742.04  5329.4 1742.50  5436.8 1744.20
  5442.3 1743.88  5534.1 1745.02  5539.6 1744.84  5561.3 1745.11  5631.5 1745.19
#Mann=4,-1,0
  4520.6   0.045       0  5010.4   0.045       0  5014.4   0.045       0
  5561.3    0.07       0
Bank Sta=5010.4,5014.4
Exp/Cntr=0.3,0.1

Type RM Length L Ch R = 1,6032,275,275,275
BEGIN DESCRIPTION:
Elm 01 53 6031.64
END DESCRIPTION:
XS GIS Cut Line= 3
      1563132.49      6863134.01      1562609.49      6863094.95
      1561975.82      6862938.70
#Sta/Elev= 30
  4471.2 1746.07  4659.2 1744.69  4769.5 1741.52  4779.5 1741.65  4819.7 1740.97
  4829.7 1741.15  4849.7 1740.73  4899.9 1740.46  4909.9 1740.10  4940.0 1739.93
  4950.0 1739.34  4960.0 1739.25  4970.1 1739.57  4980.1 1738.82  4988.1 1738.62
  4988.4 1738.12  4991.9 1738.12  4992.1 1738.62  4995.4 1739.00  5031.2 1739.63
  5217.2 1740.73  5247.5 1741.21  5278.4 1741.11  5402.0 1742.58  5443.2 1743.44
  5474.1 1743.54  5502.4 1744.09  5580.2 1744.84  5590.5 1744.62  5648.3 1745.00
#Mann=4,-1,0
  4471.2   0.045       0  4988.1   0.045       0  4992.1   0.045       0
  5580.2    0.07       0
Bank Sta=4988.1,4992.1
Exp/Cntr=0.3,0.1

Type RM Length L Ch R = 1,5757,327,327,327
BEGIN DESCRIPTION:
Elm 01 53 5756.72
END DESCRIPTION:
XS GIS Cut Line= 3
      1563023.96      6862845.38      1562555.23      6862834.53
      1561993.19      6862860.57
#Sta/Elev= 30
  4530.5 1741.36  4569.5 1740.65  4589.5 1740.58  4634.0 1739.79  4679.5 1739.35
  4839.5 1738.48  4859.5 1738.58  4899.6 1737.77  4969.6 1738.31  5002.0 1738.01
  5017.6 1737.57  5017.9 1737.07  5021.4 1737.07  5021.6 1737.57  5039.6 1737.68
  5099.7 1739.32  5209.8 1740.15  5229.8 1740.65  5309.9 1741.46  5319.9 1741.90
  5339.9 1742.02  5360.0 1742.56  5380.0 1742.56  5401.7 1743.07  5430.0 1743.16
  5460.1 1743.68  5480.1 1743.53  5490.1 1743.87  5500.4 1743.88  5562.0 1744.46
#Mann=4,-1,0
  4530.5   0.045       0  5017.6   0.045       0  5021.6   0.045       0
  5500.4    0.07       0
Bank Sta=5017.6,5021.6
Exp/Cntr=0.3,0.1

Type RM Length L Ch R = 1,5430,149,149,149
BEGIN DESCRIPTION:
Elm 01 53 5430.35
END DESCRIPTION:
XS GIS Cut Line= 3
      1562980.59      6862626.20      1562735.36      6862582.80
      1562273.11      6862606.67
#Sta/Elev= 30
  4762.1 1737.09  4835.8 1736.79  4840.9 1737.04  4909.9 1736.56  4920.1 1736.75
  4940.4 1736.62  4954.1 1736.23  4991.2 1736.19  4999.3 1735.97  4999.6 1735.47
  5003.1 1735.47  5003.3 1735.97  5008.2 1736.17  5010.6 1735.97  5015.8 1736.17
  5021.5 1735.98  5041.5 1736.29  5051.6 1736.13  5111.6 1736.76  5141.7 1736.74
  5181.7 1737.12  5191.7 1736.95  5241.8 1737.71  5271.8 1737.65  5372.0 1738.86
  5392.0 1738.76  5412.0 1739.29  5422.0 1739.09  5432.1 1739.43  5474.0 1739.73
#Mann=3,-1,0
  4762.1   0.045       0  4999.3   0.045       0  5003.3   0.045       0
Bank Sta=4999.3,5003.3
Exp/Cntr=0.3,0.1

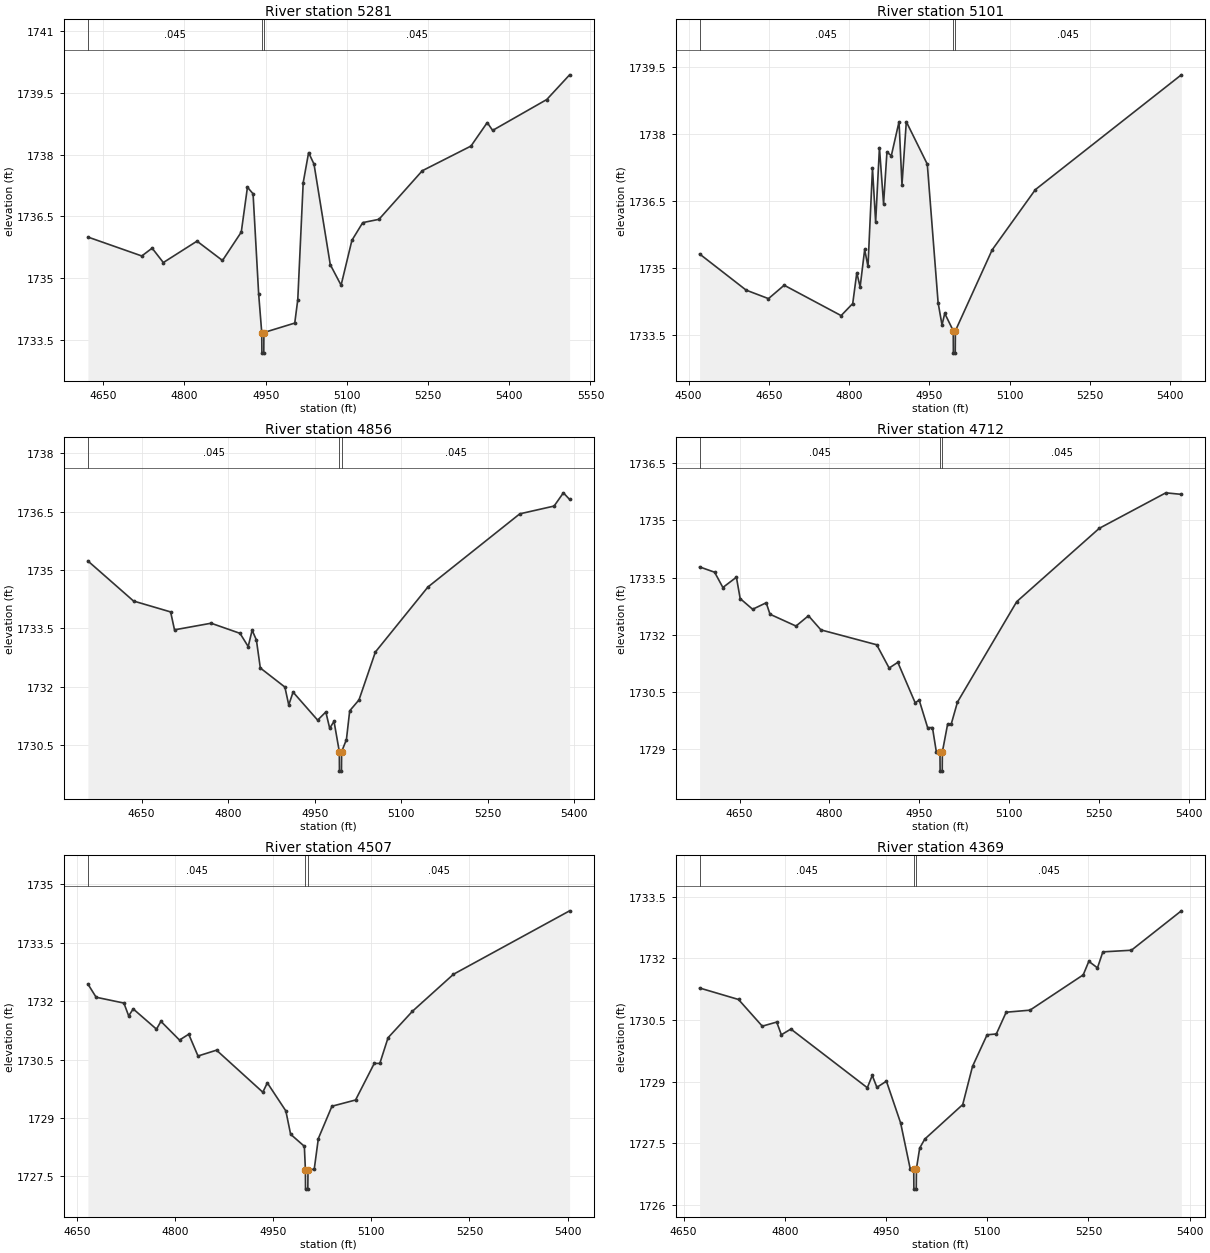
Type RM Length L Ch R = 1,5281,180,180,180
BEGIN DESCRIPTION:
Elm 01 53 5281.31
END DESCRIPTION:
XS GIS Cut Line= 3
      1563069.57      6862548.08      1562700.63      6862448.25
      1562192.85      6862446.08
#Sta/Elev= 30
  4621.5 1736.00  4721.1 1735.54  4740.2 1735.73  4760.9 1735.38  4823.1 1735.90
  4870.2 1735.43  4904.9 1736.12  4916.3 1737.21  4926.7 1737.05  4937.0 1734.62
  4942.7 1733.68  4943.0 1733.18  4946.5 1733.18  4946.7 1733.68  5003.7 1733.91
  5009.3 1734.48  5019.3 1737.32  5029.3 1738.05  5039.3 1737.77  5069.3 1735.33
  5089.3 1734.83  5109.3 1735.92  5129.3 1736.35  5159.3 1736.43  5239.3 1737.61
  5329.3 1738.21  5359.3 1738.78  5369.3 1738.59  5469.3 1739.34  5511.5 1739.94
#Mann=3,-1,0
  4621.5   0.045       0  4942.7   0.045       0  4946.7   0.045       0
Bank Sta=4942.7,4946.7
Exp/Cntr=0.3,0.1

Type RM Length L Ch R = 1,5101,245,245,245
BEGIN DESCRIPTION:
Elm 01 53 5101.35
END DESCRIPTION:
XS GIS Cut Line= 4
      1563065.25      6862498.19      1562800.46      6862302.85
      1562761.40      6862272.47      1562244.87      6862344.09
#Sta/Elev= 30
  4520.5 1735.32  4607.5 1734.51  4649.2 1734.32  4678.5 1734.62  4784.9 1733.94
  4806.6 1734.21  4814.2 1734.90  4820.4 1734.58  4828.9 1735.42  4835.1 1735.04
  4843.5 1737.24  4849.4 1736.03  4856.5 1737.70  4864.2 1736.44  4870.5 1737.60
  4878.7 1737.52  4893.1 1738.28  4898.6 1736.87  4906.7 1738.28  4945.9 1737.33
  4966.1 1734.23  4973.4 1733.73  4978.5 1733.99  4994.4 1733.60  4994.6 1733.10
  4998.1 1733.10  4998.4 1733.60  5067.0 1735.41  5147.8 1736.76  5420.5 1739.33
#Mann=3,-1,0
  4520.5   0.045       0  4994.4   0.045       0  4998.4   0.045       0
Bank Sta=4994.4,4998.4
Exp/Cntr=0.3,0.1

Type RM Length L Ch R = 1,4856,144,144,144
BEGIN DESCRIPTION:
Elm 01 53 4855.58
END DESCRIPTION:
XS GIS Cut Line= 3
      1563193.22      6862472.09      1562865.56      6862176.98
      1562519.13      6861988.61
#Sta/Elev= 30
  4556.8 1735.23  4636.0 1734.20  4700.3 1733.92  4707.0 1733.46  4770.5 1733.63
  4820.6 1733.37  4834.8 1733.03  4841.6 1733.45  4849.0 1733.20  4855.8 1732.48
  4898.4 1731.99  4905.1 1731.53  4912.6 1731.86  4955.2 1731.14  4969.4 1731.35
  4976.1 1730.93  4983.6 1731.11  4992.8 1730.33  4993.0 1729.83  4996.5 1729.83
  4996.8 1730.33  5005.1 1730.64  5010.8 1731.38  5026.9 1731.66  5055.3 1732.89
  5146.4 1734.56  5305.7 1736.44  5365.2 1736.64  5381.3 1736.98  5392.1 1736.81
#Mann=3,-1,0
  4556.8   0.045       0  4992.8   0.045       0  4996.8   0.045       0
Bank Sta=4992.8,4996.8
Exp/Cntr=0.3,0.1

Type RM Length L Ch R = 1,4712,205,205,205
BEGIN DESCRIPTION:
Elm 01 53 4712.28
END DESCRIPTION:
XS GIS Cut Line= 3
      1563314.81      6862363.63      1562984.92      6862107.54
      1562642.07      6861927.43
#Sta/Elev= 30
  4583.1 1733.78  4608.2 1733.64  4622.0 1733.24  4644.6 1733.51  4650.9 1732.95
  4671.7 1732.67  4694.4 1732.84  4700.7 1732.54  4744.2 1732.23  4765.0 1732.50
  4785.8 1732.13  4879.0 1731.74  4899.8 1731.13  4914.3 1731.28  4943.3 1730.22
  4950.0 1730.29  4964.1 1729.57  4972.2 1729.57  4978.6 1728.94  4984.7 1728.93
  4985.0 1728.43  4988.5 1728.43  4988.7 1728.93  4997.5 1729.66  5003.5 1729.66
  5014.0 1730.24  5113.0 1732.87  5250.9 1734.79  5362.1 1735.72  5388.0 1735.68
#Mann=3,-1,0
  4583.1   0.045       0  4984.7   0.045       0  4988.7   0.045       0
Bank Sta=4984.7,4988.7
Exp/Cntr=0.3,0.1

Type RM Length L Ch R = 1,4507,138,138,138
BEGIN DESCRIPTION:
Elm 01 53 4507.45
END DESCRIPTION:
XS GIS Cut Line= 3
      1563395.09      6862265.97      1563165.04      6862022.90
      1562841.68      6861784.18
#Sta/Elev= 30
  4666.5 1732.44  4679.1 1732.10  4721.6 1731.95  4728.9 1731.62  4735.8 1731.80
  4771.4 1731.28  4778.2 1731.48  4806.6 1731.00  4820.7 1731.15  4834.9 1730.59
  4863.2 1730.74  4934.0 1729.66  4940.9 1729.90  4969.2 1729.18  4976.5 1728.58
  4997.5 1728.27  4999.1 1727.67  4999.3 1727.17  5002.8 1727.17  5003.1 1727.67
  5012.6 1727.68  5018.9 1728.47  5039.7 1729.30  5075.8 1729.46  5104.4 1730.40
  5112.9 1730.40  5125.5 1731.06  5162.8 1731.74  5225.5 1732.69  5403.1 1734.32
#Mann=3,-1,0
  4666.5   0.045       0  4999.1   0.045       0  5003.1   0.045       0
Bank Sta=4999.1,5003.1
Exp/Cntr=0.3,0.1

Type RM Length L Ch R = 1,4369,186,186,186
BEGIN DESCRIPTION:
Elm 01 53 4369.29
END DESCRIPTION:
XS GIS Cut Line= 3
      1563520.96      6862183.50      1563280.06      6861955.63
      1562976.24      6861723.42
#Sta/Elev= 30
  4673.7 1731.28  4731.4 1731.00  4766.6 1730.35  4788.0 1730.45  4794.9 1730.14
  4809.0 1730.28  4922.3 1728.85  4929.6 1729.15  4936.5 1728.86  4950.6 1729.01
  4971.7 1727.99  4985.8 1726.88  4991.1 1726.88  4991.3 1726.38  4994.8 1726.38
  4995.1 1726.88  4999.9 1727.38  5007.5 1727.60  5063.7 1728.44  5078.2 1729.37
  5099.8 1730.14  5113.5 1730.16  5128.1 1730.69  5163.4 1730.74  5242.3 1731.60
  5250.6 1731.93  5263.4 1731.77  5271.4 1732.16  5313.7 1732.20  5387.7 1733.16
#Mann=3,-1,0
  4673.7   0.045       0  4991.1   0.045       0  4995.1   0.045       0
Bank Sta=4991.1,4995.1
Exp/Cntr=0.3,0.1

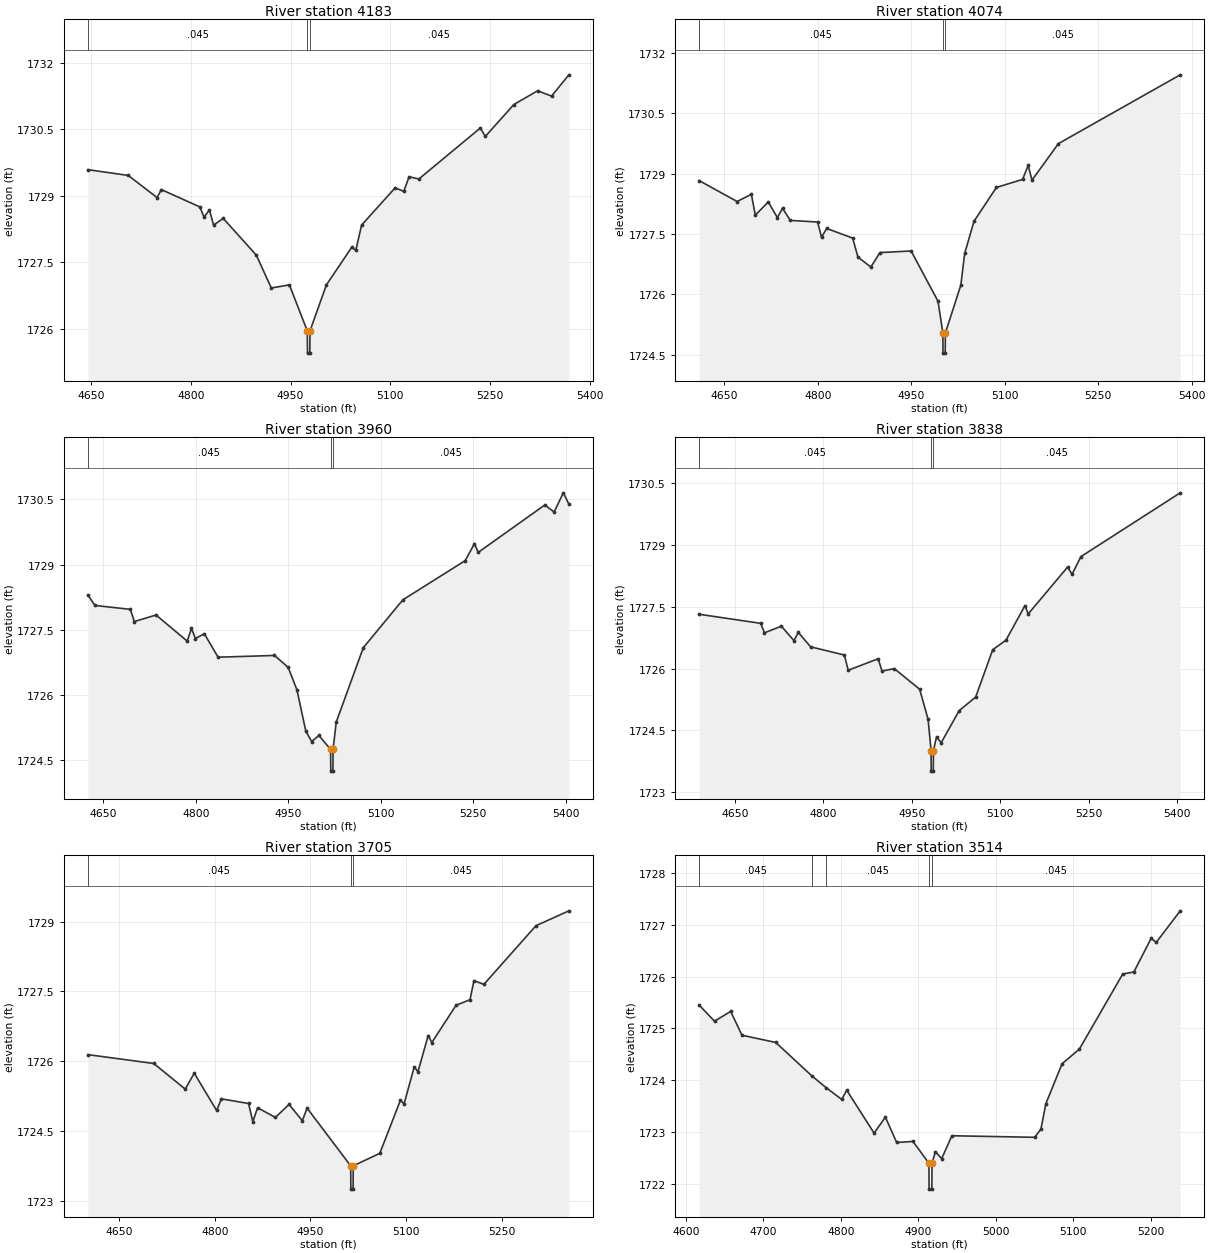
Type RM Length L Ch R = 1,4183,109,109,109
BEGIN DESCRIPTION:
Elm 01 53 4183.31
END DESCRIPTION:
XS GIS Cut Line= 3
      1563711.92      6862077.15      1563429.80      6861855.80
      1563132.48      6861645.28
#Sta/Elev= 30
  4645.3 1729.59  4706.0 1729.46  4749.3 1728.96  4755.8 1729.14  4813.5 1728.75
  4819.9 1728.52  4828.0 1728.68  4834.3 1728.34  4848.8 1728.49  4898.5 1727.66
  4921.0 1726.92  4948.2 1726.99  4975.1 1725.95  4975.4 1725.45  4978.9 1725.45
  4979.1 1725.95  5003.8 1726.99  5041.9 1727.84  5048.0 1727.77  5056.7 1728.34
  5107.1 1729.18  5120.1 1729.10  5128.0 1729.43  5142.8 1729.38  5235.1 1730.53
  5242.6 1730.34  5285.5 1731.06  5321.2 1731.37  5342.1 1731.25  5368.2 1731.73
#Mann=3,-1,0
  4645.3   0.045       0  4975.1   0.045       0  4979.1   0.045       0
Bank Sta=4975.1,4979.1
Exp/Cntr=0.3,0.1

Type RM Length L Ch R = 1,4074,114,114,114
BEGIN DESCRIPTION:
Elm 01 53 4073.88
END DESCRIPTION:
XS GIS Cut Line= 3
      1563792.22      6861996.86      1563475.37      6861760.31
      1563162.87      6861549.81
#Sta/Elev= 30
  4609.5 1728.83  4670.4 1728.31  4693.3 1728.49  4699.6 1727.97  4720.4 1728.30
  4735.0 1727.91  4743.3 1728.14  4755.9 1727.84  4799.6 1727.80  4805.9 1727.42
  4814.2 1727.64  4855.9 1727.40  4864.3 1726.93  4885.1 1726.68  4899.7 1727.04
  4949.7 1727.08  4992.9 1725.83  5000.7 1725.04  5000.9 1724.54  5004.4 1724.54
  5004.7 1725.04  5029.5 1726.23  5035.7 1727.02  5050.7 1727.82  5086.7 1728.66
  5128.7 1728.86  5137.6 1729.21  5143.7 1728.84  5186.2 1729.75  5381.7 1731.46
#Mann=3,-1,0
  4609.5   0.045       0  5000.7   0.045       0  5004.7   0.045       0
Bank Sta=5000.7,5004.7
Exp/Cntr=0.3,0.1

Type RM Length L Ch R = 1,3960,122,122,122
BEGIN DESCRIPTION:
Elm 01 53 3959.66
END DESCRIPTION:
XS GIS Cut Line= 3
      1563870.31      6861949.09      1563586.05      6861719.08
      1563240.97      6861489.02
#Sta/Elev= 30
  4624.7 1728.30  4636.2 1728.06  4693.7 1727.97  4700.1 1727.69  4735.3 1727.84
  4785.9 1727.24  4792.8 1727.53  4799.3 1727.30  4813.7 1727.41  4836.0 1726.87
  4927.4 1726.91  4949.5 1726.64  4963.9 1726.12  4978.3 1725.17  4987.8 1724.93
  4999.5 1725.07  5018.5 1724.75  5018.8 1724.25  5022.3 1724.25  5022.5 1724.75
  5027.7 1725.38  5071.6 1727.09  5135.8 1728.19  5236.8 1729.09  5251.9 1729.48
  5257.9 1729.28  5366.0 1730.37  5381.1 1730.21  5396.1 1730.65  5405.1 1730.39
#Mann=3,-1,0
  4624.7   0.045       0  5018.5   0.045       0  5022.5   0.045       0
Bank Sta=5018.5,5022.5
Exp/Cntr=0.3,0.1

Type RM Length L Ch R = 1,3838,133,133,133
BEGIN DESCRIPTION:
Elm 01 53 3837.56
END DESCRIPTION:
XS GIS Cut Line= 3
      1563948.49      6861871.01      1563635.96      6861610.57
      1563271.39      6861426.12
#Sta/Elev= 30
  4589.5 1727.32  4693.7 1727.10  4700.2 1726.87  4728.8 1727.03  4750.2 1726.68
  4757.5 1726.88  4778.3 1726.53  4835.6 1726.33  4842.1 1725.96  4892.9 1726.24
  4899.4 1725.94  4920.2 1726.00  4963.2 1725.50  4977.5 1724.77  4982.6 1724.01
  4982.8 1723.51  4986.3 1723.51  4986.6 1724.01  4991.8 1724.34  4999.7 1724.20
  5030.3 1724.98  5058.2 1725.31  5087.1 1726.46  5109.5 1726.69  5141.7 1727.53
  5147.3 1727.33  5214.2 1728.47  5221.5 1728.29  5236.5 1728.72  5404.9 1730.27
#Mann=3,-1,0
  4589.5   0.045       0  4982.6   0.045       0  4986.6   0.045       0
Bank Sta=4982.6,4986.6
Exp/Cntr=0.3,0.1

Type RM Length L Ch R = 1,3705,191,191,191
BEGIN DESCRIPTION:
Elm 01 53 3705.32
END DESCRIPTION:
XS GIS Cut Line= 3
      1563994.06      6861764.68      1563698.90      6861499.90
      1563384.20      6861328.44
#Sta/Elev= 30
  4600.6 1726.14  4704.0 1725.95  4753.4 1725.40  4767.6 1725.74  4802.7 1724.94
  4810.2 1725.19  4852.8 1725.09  4859.5 1724.70  4867.0 1725.00  4894.9 1724.79
  4916.3 1725.07  4937.2 1724.72  4944.7 1724.99  5013.1 1723.75  5013.3 1723.25
  5016.8 1723.25  5017.1 1723.75  5058.8 1724.02  5091.1 1725.16  5096.8 1725.08
  5112.9 1725.88  5118.6 1725.77  5134.7 1726.55  5140.4 1726.40  5178.4 1727.20
  5200.3 1727.32  5206.5 1727.73  5222.1 1727.65  5303.8 1728.91  5355.5 1729.23
#Mann=3,-1,0
  4600.6   0.045       0  5013.1   0.045       0  5017.1   0.045       0
Bank Sta=5013.1,5017.1
Exp/Cntr=0.3,0.1

Type RM Length L Ch R = 1,3514,222,222,222
BEGIN DESCRIPTION:
Elm 01 53 3514.09
END DESCRIPTION:
XS GIS Cut Line= 3
      1564063.03      6861667.41      1563830.41      6861361.88
      1563646.68      6861212.81
#Sta/Elev= 30
  4617.3 1725.45  4637.1 1725.14  4657.9 1725.33  4672.5 1724.87  4716.1 1724.73
  4763.0 1724.08  4780.9 1723.86  4801.3 1723.63  4807.6 1723.81  4843.0 1722.98
  4857.5 1723.29  4872.1 1722.80  4893.1 1722.82  4913.7 1722.40  4913.9 1721.90
  4917.4 1721.90  4917.7 1722.40  4922.0 1722.62  4930.2 1722.49  4943.3 1722.93
  5050.2 1722.90  5058.2 1723.06  5064.6 1723.55  5085.5 1724.32  5107.7 1724.60
  5163.7 1726.05  5178.1 1726.09  5200.4 1726.74  5206.9 1726.66  5237.9 1727.27
#Mann=5,-1,0
  4617.3   0.045       0  4763.0    0.07       0  4780.9   0.045       0
  4913.7   0.045       0  4917.7   0.045       0
Bank Sta=4913.7,4917.7
Exp/Cntr=0.3,0.1

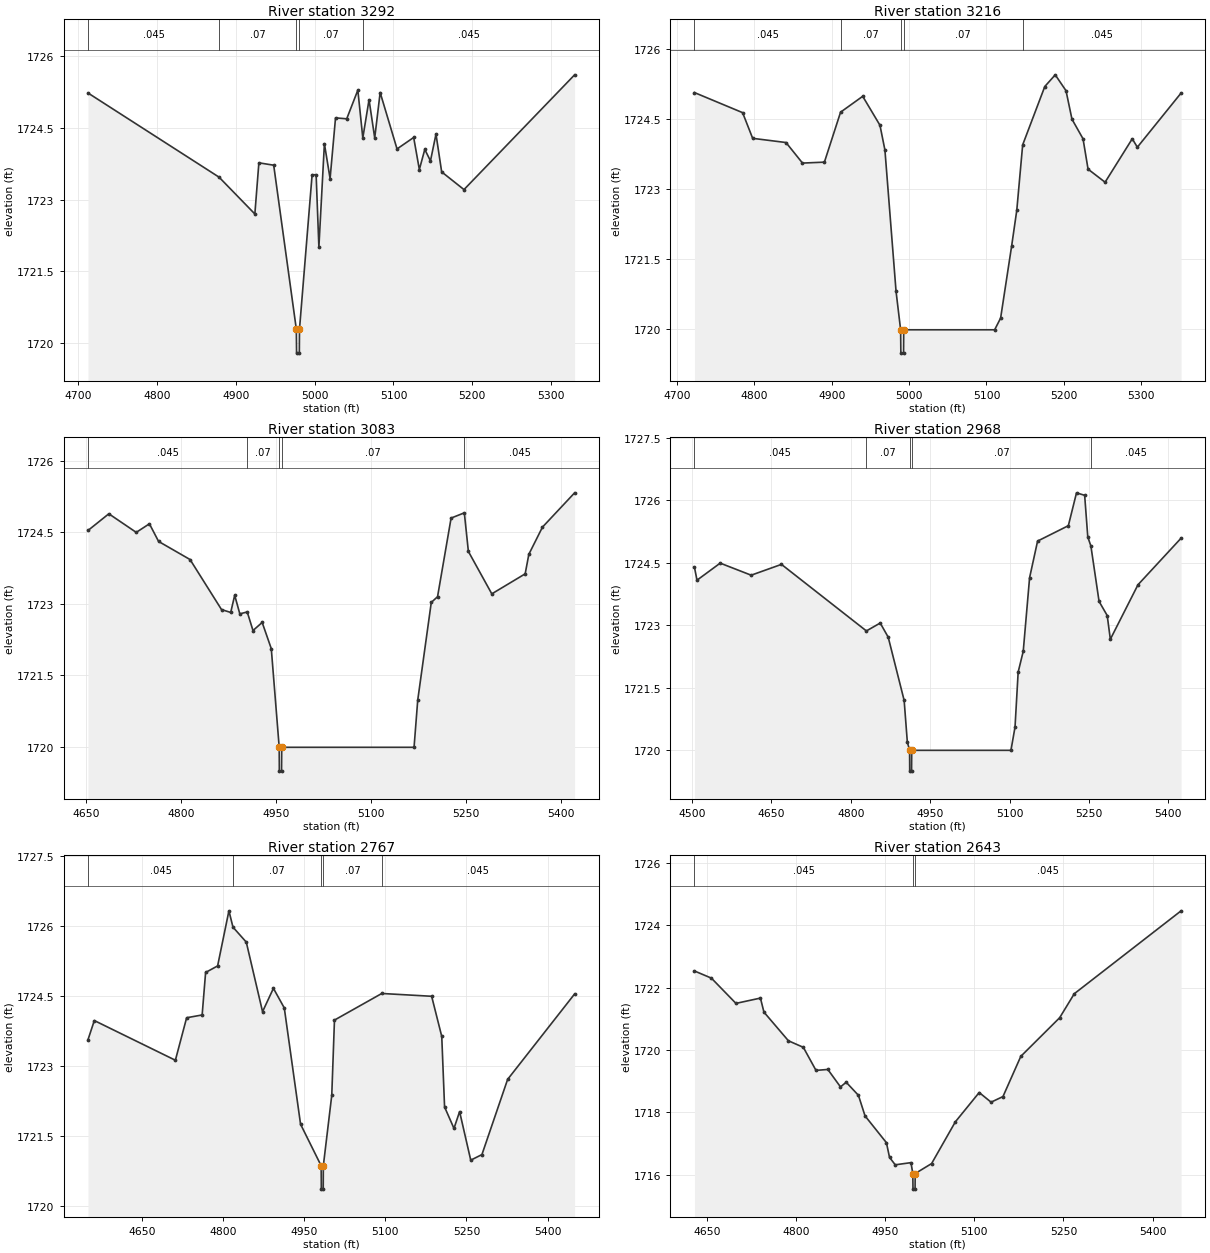
Type RM Length L Ch R = 1,3292,76,76,76
BEGIN DESCRIPTION:
Elm 01 53 3291.97
END DESCRIPTION:
XS GIS Cut Line= 3
      1564097.78      6861667.48      1564033.53      6861387.92
      1563795.71      6861158.77
#Sta/Elev= 30
  4712.6 1725.23  4878.8 1723.47  4924.2 1722.70  4929.3 1723.77  4948.1 1723.72
  4976.8 1720.29  4977.1 1719.79  4980.6 1719.79  4980.8 1720.29  4996.8 1723.52
  5001.9 1723.52  5005.4 1722.01  5012.4 1724.17  5019.6 1723.44  5026.5 1724.71
  5040.7 1724.69  5054.8 1725.29  5061.1 1724.29  5069.0 1725.09  5076.2 1724.29
  5083.1 1725.24  5104.5 1724.06  5125.6 1724.30  5132.8 1723.63  5139.7 1724.05
  5146.9 1723.81  5153.9 1724.37  5161.1 1723.58  5189.4 1723.21  5329.7 1725.61
#Mann=5,-1,0
  4712.6   0.045       0  4878.8    0.07       0  4976.8    0.07       0
  4980.8    0.07       0  5061.1   0.045       0
Bank Sta=4976.8,4980.8
Exp/Cntr=0.3,0.1

Type RM Length L Ch R = 1,3216,133,133,133
BEGIN DESCRIPTION:
Elm 01 53 3215.5
END DESCRIPTION:
XS GIS Cut Line= 3
      1564283.51      6861596.22      1564108.19      6861380.97
      1563841.55      6861152.43
#Sta/Elev= 30
  4722.7 1725.07  4784.9 1724.64  4797.9 1724.09  4841.0 1724.00  4862.3 1723.56
  4890.6 1723.58  4911.5 1724.65  4940.1 1724.99  4962.4 1724.37  4968.8 1723.84
  4983.2 1720.81  4989.1 1719.99  4989.4 1719.49  4992.9 1719.49  4993.1 1719.99
  5110.6 1719.99  5118.3 1720.24  5132.6 1721.79  5139.2 1722.55  5146.8 1723.95
  5175.4 1725.20  5188.9 1725.45  5202.8 1725.11  5210.5 1724.50  5224.8 1724.08
  5231.3 1723.43  5253.3 1723.15  5288.4 1724.08  5295.0 1723.90  5351.5 1725.06
#Mann=5,-1,0
  4722.7   0.045       0  4911.5    0.07       0  4989.1    0.07       0
  4993.1    0.07       0  5146.8   0.045       0
Bank Sta=4989.1,4993.1
Exp/Cntr=0.3,0.1

Type RM Length L Ch R = 1,3083,115,115,115
BEGIN DESCRIPTION:
Elm 01 53 3082.63
END DESCRIPTION:
XS GIS Cut Line= 3
      1564495.31      6861533.73      1564227.98      6861323.68
      1563859.07      6861105.45
#Sta/Elev= 30
  4653.2 1724.54  4686.1 1724.89  4729.4 1724.50  4750.2 1724.68  4764.7 1724.31
  4814.4 1723.93  4864.1 1722.88  4878.6 1722.82  4884.9 1723.18  4893.0 1722.79
  4904.7 1722.83  4913.8 1722.44  4928.3 1722.61  4942.7 1722.06  4955.2 1719.99
  4955.4 1719.49  4958.9 1719.49  4959.2 1719.99  5168.2 1719.99  5174.0 1720.98
  5195.4 1723.03  5205.3 1723.15  5226.7 1724.80  5247.6 1724.91  5254.0 1724.10
  5291.0 1723.21  5343.7 1723.63  5349.5 1724.04  5371.0 1724.61  5421.8 1725.33
#Mann=5,-1,0
  4653.2   0.045       0  4904.7    0.07       0  4955.2    0.07       0
  4959.2    0.07       0  5247.6   0.045       0
Bank Sta=4955.2,4959.2
Exp/Cntr=0.3,0.1

Type RM Length L Ch R = 1,2968,201,201,201
BEGIN DESCRIPTION:
Elm 01 53 2968.35
END DESCRIPTION:
XS GIS Cut Line= 3
      1564685.57      6861494.56      1564274.85      6861222.99
      1563911.04      6861000.19
#Sta/Elev= 30
  4504.9 1724.39  4509.7 1724.08  4553.5 1724.49  4612.0 1724.20  4669.2 1724.46
  4829.6 1722.86  4855.7 1723.05  4870.8 1722.71  4900.9 1721.19  4906.9 1720.19
  4911.2 1719.99  4911.4 1719.49  4914.9 1719.49  4915.2 1719.99  5102.6 1719.99
  5110.3 1720.55  5116.2 1721.87  5125.8 1722.37  5137.8 1724.14  5152.9 1725.02
  5211.0 1725.39  5226.4 1726.18  5241.8 1726.12  5247.7 1725.12  5253.6 1724.90
  5269.0 1723.57  5284.4 1723.23  5290.3 1722.66  5342.5 1723.97  5423.9 1725.09
#Mann=5,-1,0
  4504.9   0.045       0  4829.6    0.07       0  4911.2    0.07       0
  4915.2    0.07       0  5253.6   0.045       0
Bank Sta=4911.2,4915.2
Exp/Cntr=0.3,0.1

Type RM Length L Ch R = 1,2767,124,124,124
BEGIN DESCRIPTION:
Elm 01 53 2762.72
END DESCRIPTION:
XS GIS Cut Line= 4
      1564735.30      6861304.61      1564556.19      6861087.43
      1564258.29      6861062.31      1563949.07      6860982.16
#Sta/Elev= 30
  4550.2 1723.57  4561.9 1723.98  4711.8 1723.13  4732.6 1724.04  4761.3 1724.10
  4767.7 1725.01  4789.9 1725.15  4810.8 1726.33  4818.3 1725.98  4842.9 1725.66
  4873.0 1724.17  4893.1 1724.67  4913.2 1724.25  4943.3 1721.76  4981.4 1720.87
  4981.7 1720.37  4985.2 1720.37  4985.4 1720.87  5001.0 1722.38  5006.0 1723.99
  5093.5 1724.56  5185.7 1724.50  5204.4 1723.64  5209.6 1722.13  5227.0 1721.67
  5237.4 1722.03  5258.0 1720.99  5278.7 1721.11  5326.2 1722.72  5450.1 1724.55
#Mann=5,-1,0
  4550.2   0.045       0  4818.3    0.07       0  4981.4    0.07       0
  4985.4    0.07       0  5093.5   0.045       0
Bank Sta=4981.4,4985.4
Exp/Cntr=0.3,0.1

Type RM Length L Ch R = 1,2643,246,246,246
BEGIN DESCRIPTION:
Elm 01 53 2643.29
END DESCRIPTION:
XS GIS Cut Line= 3
      1564762.69      6861061.53      1564394.64      6860969.52
      1563955.39      6860957.36
#Sta/Elev= 30
  4629.2 1722.54  4657.7 1722.31  4699.0 1721.50  4740.2 1721.67  4746.1 1721.22
  4787.3 1720.30  4812.4 1720.09  4833.7 1719.35  4853.6 1719.38  4874.9 1718.82
  4884.5 1718.97  4905.1 1718.55  4916.2 1717.89  4952.2 1717.03  4957.4 1716.56
  4967.0 1716.32  4993.5 1716.39  4996.6 1716.04  4996.9 1715.54  5000.4 1715.54
  5000.6 1716.04  5028.2 1716.36  5068.2 1717.70  5108.3 1718.64  5128.3 1718.33
  5148.3 1718.51  5178.3 1719.80  5243.7 1721.04  5268.3 1721.81  5448.0 1724.47
#Mann=3,-1,0
  4629.2   0.045       0  4996.6   0.045       0  5000.6   0.045       0
Bank Sta=4996.6,5000.6
Exp/Cntr=0.3,0.1

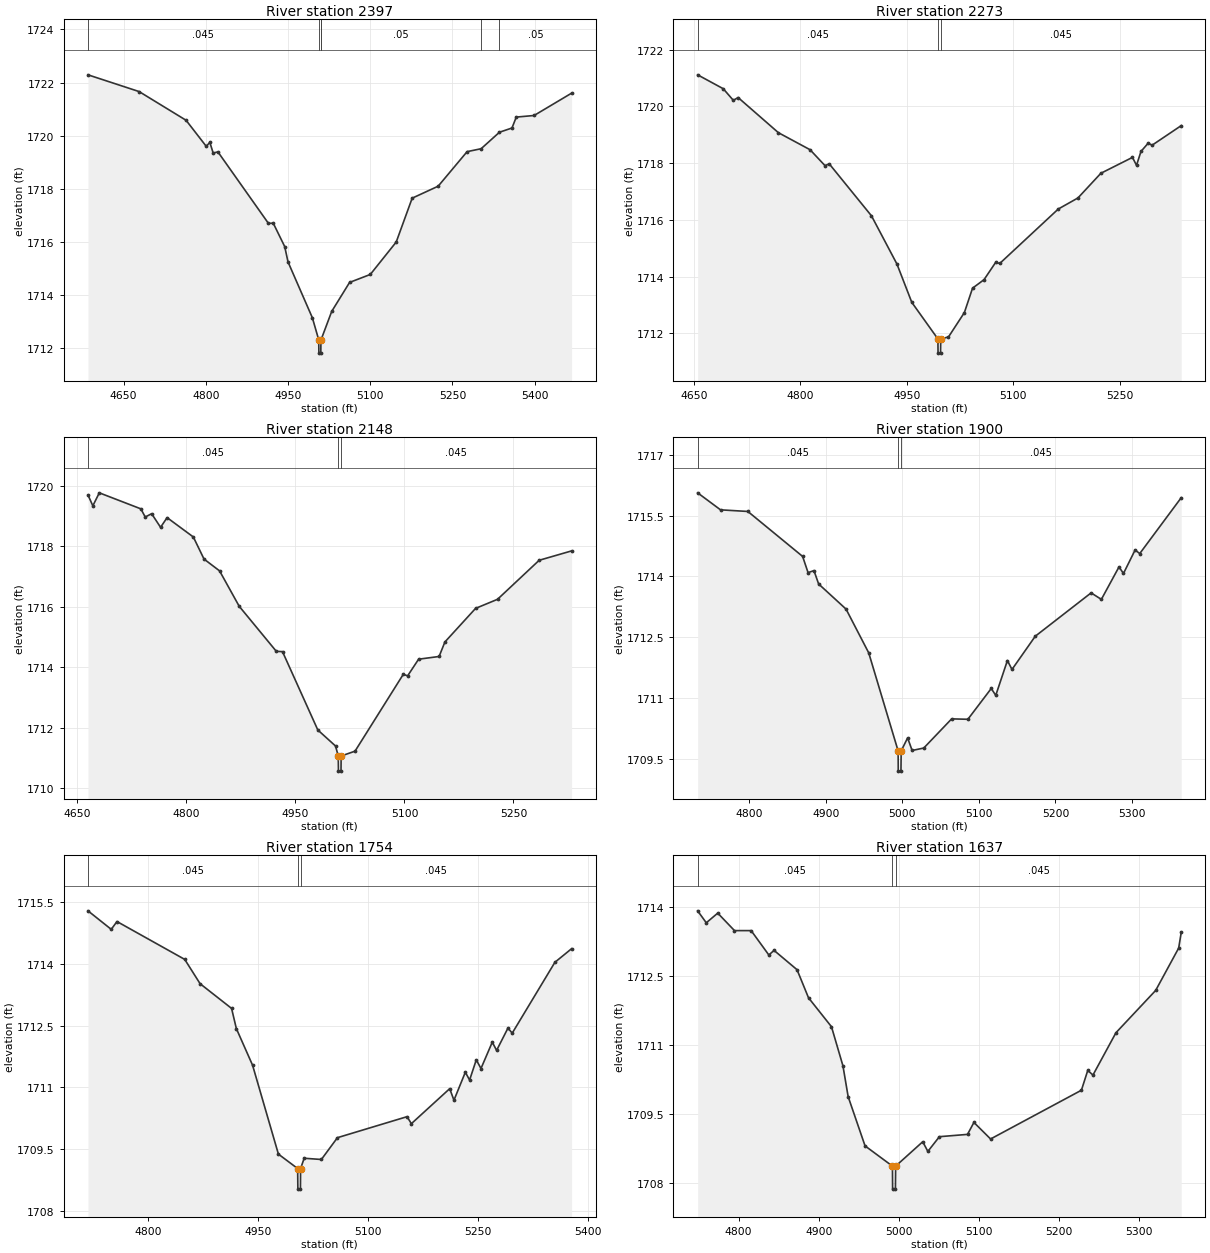
Type RM Length L Ch R = 1,2397,124,124,124
BEGIN DESCRIPTION:
Elm 01 53 2396.606
END DESCRIPTION:
XS GIS Cut Line= 3
      1564891.16      6861021.59      1564552.46      6860781.95
      1564122.05      6860599.71
#Sta/Elev= 30
  4585.1 1722.29  4678.4 1721.66  4764.1 1720.58  4800.9 1719.60  4807.4 1719.75
  4813.5 1719.35  4822.2 1719.39  4914.4 1716.70  4923.1 1716.71  4944.0 1715.83
  4950.1 1715.25  4994.5 1713.15  5006.1 1712.32  5006.4 1711.82  5009.9 1711.82
  5010.1 1712.32  5010.5 1712.33  5029.8 1713.39  5062.4 1714.48  5100.2 1714.78
  5147.5 1716.00  5176.6 1717.65  5224.0 1718.10  5276.8 1719.40  5302.4 1719.51
  5335.8 1720.13  5358.7 1720.29  5366.5 1720.70  5399.0 1720.76  5467.4 1721.60
#Mann=6,-1,0
  4585.1   0.045       0  5006.1   0.045       0  5010.1   0.045       0
  5010.5    0.05       0  5302.4   0.045       0  5335.8    0.05       0
Bank Sta=5006.1,5010.1
Exp/Cntr=0.3,0.1

Type RM Length L Ch R = 1,2273,125,125,125
BEGIN DESCRIPTION:
Elm 01 53 2273.25
END DESCRIPTION:
XS GIS Cut Line= 3
      1564896.41      6860875.79      1564615.13      6860681.32
      1564314.81      6860523.35
#Sta/Elev= 30
  4655.4 1721.11  4691.5 1720.62  4705.7 1720.21  4712.4 1720.31  4769.2 1719.07
  4813.8 1718.47  4834.8 1717.91  4840.9 1717.97  4900.3 1716.14  4936.2 1714.44
  4957.1 1713.09  4993.9 1711.80  4994.1 1711.30  4997.6 1711.30  4997.9 1711.80
  5008.8 1711.87  5031.2 1712.73  5042.7 1713.59  5058.9 1713.89  5075.3 1714.50
  5081.0 1714.46  5163.5 1716.38  5191.2 1716.77  5223.5 1717.64  5268.0 1718.20
  5273.7 1717.92  5280.0 1718.41  5290.1 1718.70  5295.7 1718.63  5336.7 1719.32
#Mann=3,-1,0
  4655.4   0.045       0  4993.9   0.045       0  4997.9   0.045       0
Bank Sta=4993.9,4997.9
Exp/Cntr=0.3,0.1

Type RM Length L Ch R = 1,2148,248,248,248
BEGIN DESCRIPTION:
Elm 01 53 2148.02
END DESCRIPTION:
XS GIS Cut Line= 3
      1564977.99      6860775.08      1564698.46      6860589.31
      1564422.40      6860408.74
#Sta/Elev= 30
  4664.5 1719.69  4671.2 1719.33  4680.1 1719.76  4737.3 1719.23  4743.3 1718.96
  4752.1 1719.07  4764.4 1718.62  4773.4 1718.94  4809.5 1718.30  4824.2 1717.57
  4845.6 1717.18  4872.6 1716.01  4923.7 1714.52  4932.2 1714.51  4980.8 1711.92
  5005.2 1711.39  5008.9 1711.06  5009.2 1710.56  5012.7 1710.56  5012.9 1711.06
  5032.0 1711.22  5098.4 1713.76  5104.4 1713.71  5119.5 1714.26  5147.7 1714.35
  5155.7 1714.83  5197.9 1715.94  5228.1 1716.24  5285.4 1717.53  5330.0 1717.84
#Mann=3,-1,0
  4664.5   0.045       0  5008.9   0.045       0  5012.9   0.045       0
Bank Sta=5008.9,5012.9
Exp/Cntr=0.3,0.1

Type RM Length L Ch R = 1,1900,146,146,146
BEGIN DESCRIPTION:
Elm 01 53 1900.436
END DESCRIPTION:
XS GIS Cut Line= 3
      1565063.08      6860551.14      1564844.22      6860397.68
      1564536.97      6860202.13
#Sta/Elev= 30
  4732.7 1716.06  4762.6 1715.64  4798.3 1715.60  4869.8 1714.49  4876.9 1714.09
  4884.6 1714.14  4890.7 1713.81  4926.5 1713.19  4956.1 1712.11  4994.5 1709.69
  4994.7 1709.19  4998.2 1709.19  4998.5 1709.69  5006.9 1710.01  5012.8 1709.70
  5028.0 1709.76  5064.4 1710.48  5085.6 1710.47  5116.1 1711.23  5122.0 1711.06
  5137.2 1711.92  5143.2 1711.70  5173.6 1712.52  5246.5 1713.59  5259.9 1713.43
  5282.9 1714.23  5288.8 1714.07  5304.0 1714.65  5310.0 1714.56  5364.2 1715.94
#Mann=3,-1,0
  4732.7   0.045       0  4994.5   0.045       0  4998.5   0.045       0
Bank Sta=4994.5,4998.5
Exp/Cntr=0.3,0.1

Type RM Length L Ch R = 1,1754,117,117,117
BEGIN DESCRIPTION:
Elm 01 53 1753.99
END DESCRIPTION:
XS GIS Cut Line= 3
      1565097.76      6860490.34      1564920.69      6860278.54
      1564594.28      6860078.88
#Sta/Elev= 30
  4718.4 1715.29  4750.1 1714.84  4757.9 1715.03  4850.2 1714.11  4871.1 1713.52
  4914.0 1712.92  4920.5 1712.43  4942.6 1711.54  4977.8 1709.38  5004.0 1709.03
  5004.3 1708.53  5007.8 1708.53  5008.0 1709.03  5012.9 1709.28  5036.3 1709.25
  5058.2 1709.78  5153.0 1710.29  5158.9 1710.12  5211.1 1710.97  5216.9 1710.69
  5232.4 1711.37  5238.2 1711.18  5247.3 1711.67  5253.7 1711.46  5269.1 1712.10
  5275.0 1711.90  5290.4 1712.44  5296.3 1712.32  5354.4 1714.04  5377.1 1714.37
#Mann=3,-1,0
  4718.4   0.045       0  5004.0   0.045       0  5008.0   0.045       0
Bank Sta=5004,5008
Exp/Cntr=0.3,0.1

Type RM Length L Ch R = 1,1637,177,177,177
BEGIN DESCRIPTION:
Elm 01 53 1636.84
END DESCRIPTION:
XS GIS Cut Line= 3
      1565129.00      6860368.80      1564967.56      6860174.38
      1564695.53      6859952.59
#Sta/Elev= 30
  4748.8 1713.91  4759.6 1713.65  4773.9 1713.86  4794.8 1713.48  4815.6 1713.48
  4837.7 1712.95  4844.2 1713.05  4872.9 1712.63  4887.2 1712.02  4915.9 1711.39
  4930.2 1710.54  4936.7 1709.87  4957.8 1708.80  4992.0 1708.36  4992.2 1707.86
  4995.7 1707.86  4996.0 1708.36  5029.8 1708.89  5036.2 1708.68  5050.6 1709.00
  5085.7 1709.05  5093.7 1709.31  5114.5 1708.95  5227.9 1710.01  5235.8 1710.44
  5242.3 1710.34  5271.0 1711.26  5320.6 1712.18  5349.3 1713.10  5352.5 1713.44
#Mann=3,-1,0
  4748.8   0.045       0  4992.0   0.045       0  4996.0   0.045       0
Bank Sta=4992,4996
Exp/Cntr=0.3,0.1