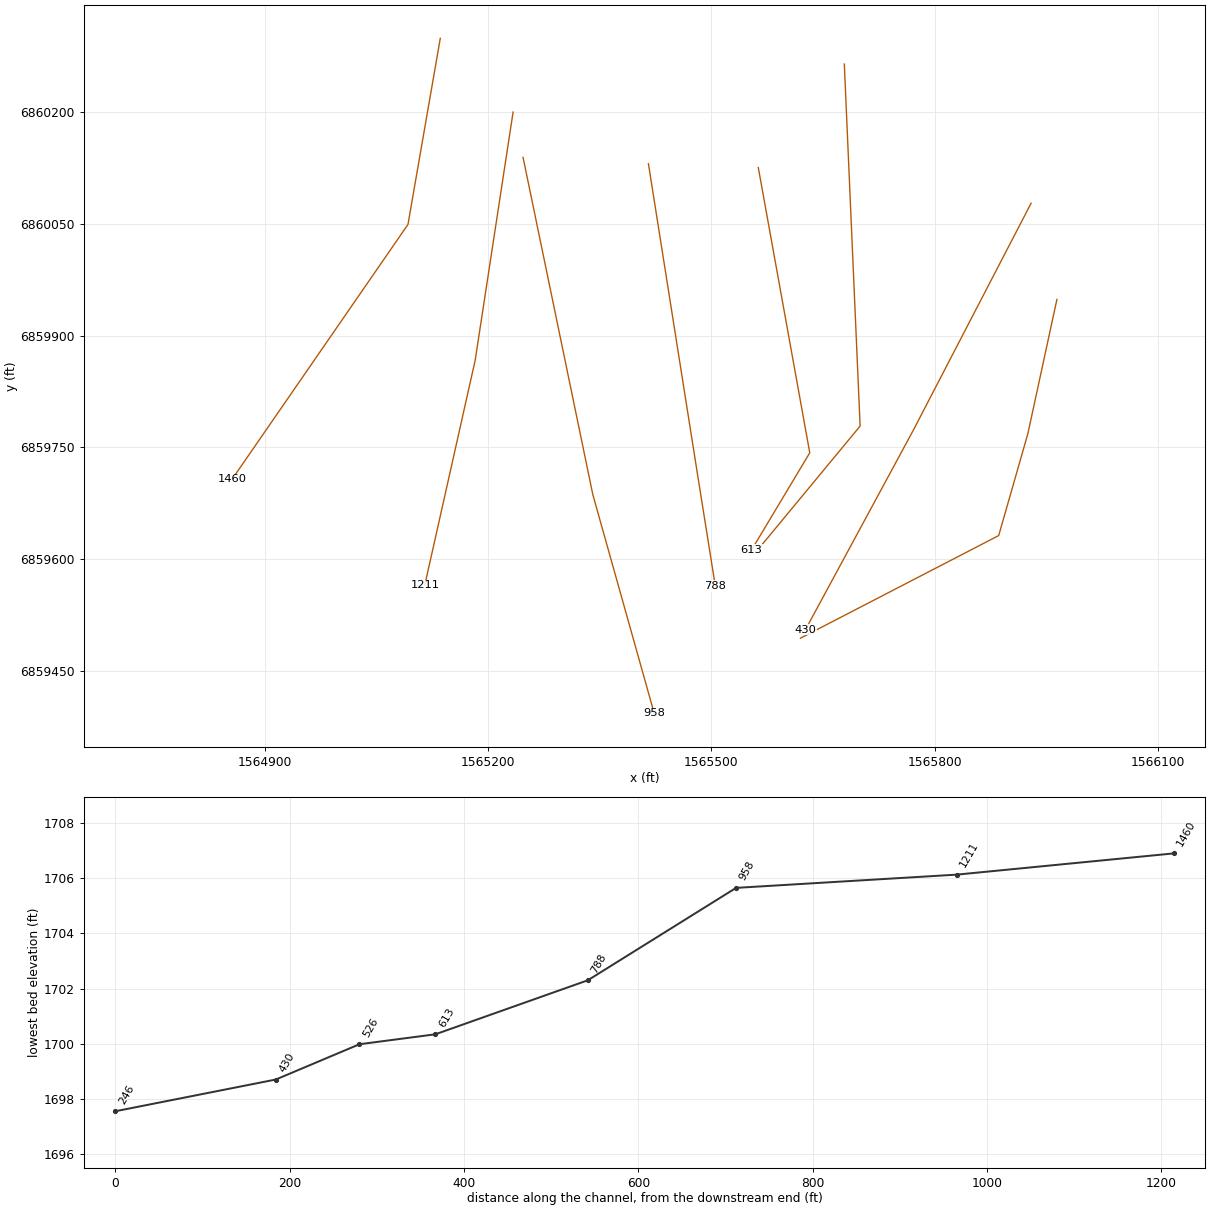
HEC-RAS study Elm 01 53.prj: Elm 01 53 Base Level Engineering

--- Elm 01 53.g01 (geometry) --- (continued)

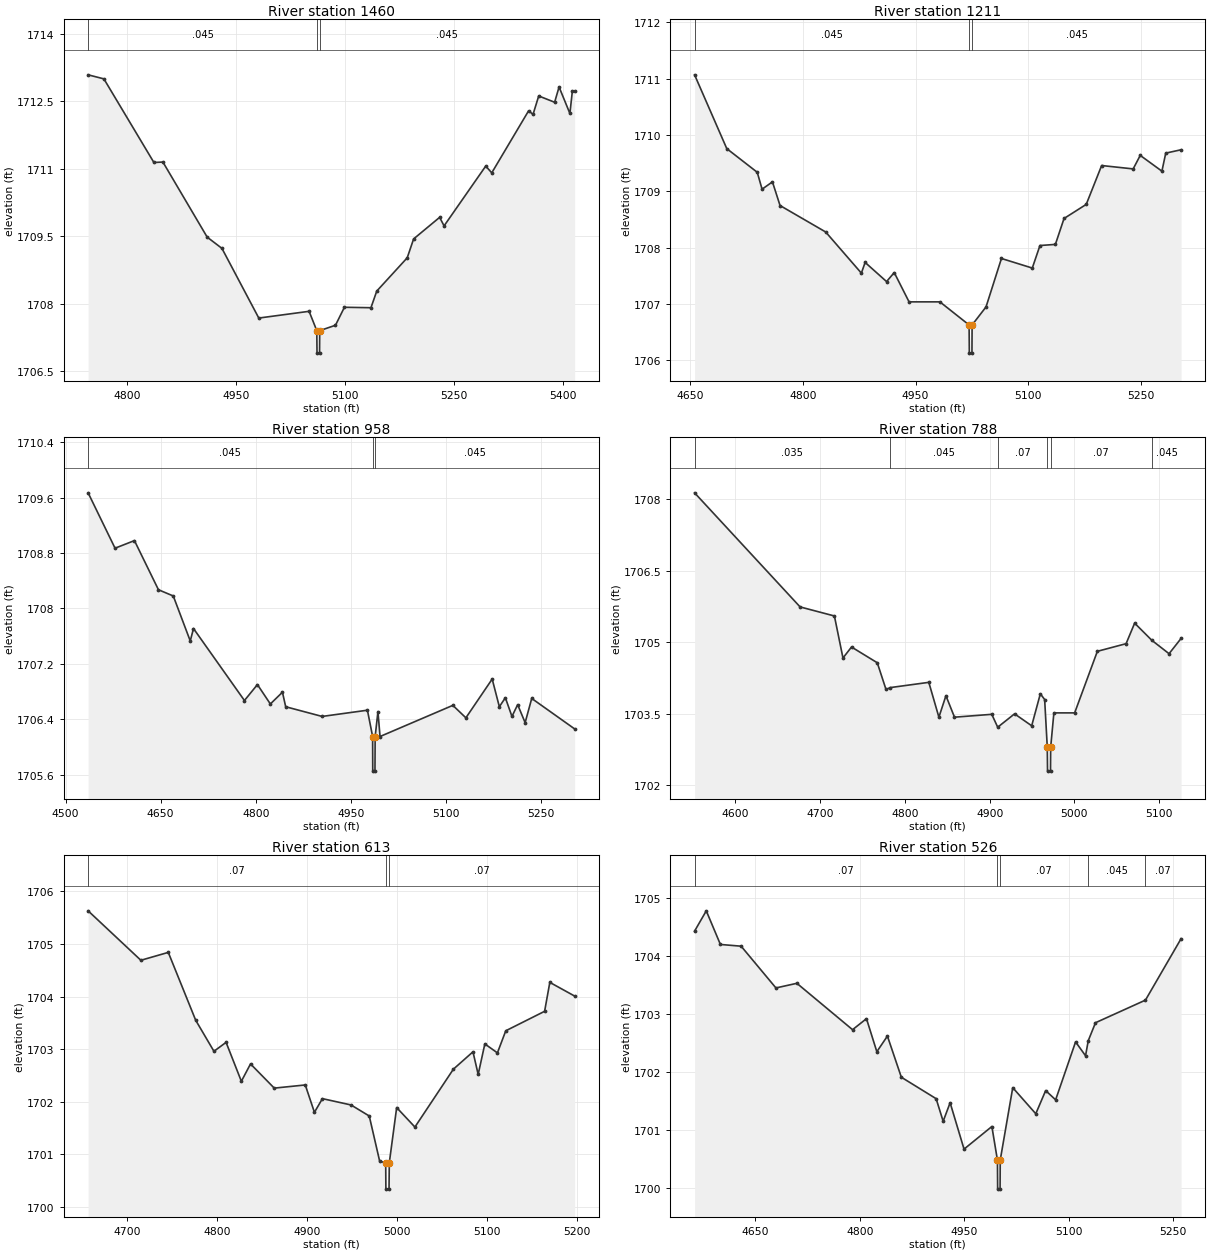
Type RM Length L Ch R = 1,1460,249,249,249
BEGIN DESCRIPTION:
Elm 01 53 1460.17
END DESCRIPTION:
XS GIS Cut Line= 3
      1565135.96      6860299.36      1565092.56      6860049.38
      1564856.46      6859707.38
#Sta/Elev= 30
  4746.7 1713.09  4768.4 1713.00  4837.2 1711.14  4849.6 1711.15  4910.5 1709.48
  4930.8 1709.23  4981.5 1707.68  5050.7 1707.83  5061.3 1707.40  5061.6 1706.90
  5065.1 1706.90  5065.3 1707.40  5087.0 1707.52  5099.3 1707.92  5135.8 1707.91
  5143.8 1708.28  5185.7 1709.02  5194.5 1709.44  5230.3 1709.92  5236.4 1709.73
  5293.7 1711.06  5302.0 1710.91  5352.7 1712.29  5358.8 1712.21  5366.6 1712.62
  5388.5 1712.48  5394.6 1712.82  5409.5 1712.23  5412.9 1712.73  5416.0 1712.73
#Mann=3,-1,0
  4746.7   0.045       0  5061.3   0.045       0  5065.3   0.045       0
Bank Sta=5061.3,5065.3
Exp/Cntr=0.3,0.1

Type RM Length L Ch R = 1,1211,253,253,253
BEGIN DESCRIPTION:
Elm 01 53 1210.99
END DESCRIPTION:
XS GIS Cut Line= 3
      1565233.75      6860200.32      1565182.84      6859867.08
      1565115.13      6859564.98
#Sta/Elev= 30
  4656.3 1711.07  4699.1 1709.76  4739.6 1709.34  4746.0 1709.04  4759.8 1709.17
  4769.9 1708.75  4830.6 1708.28  4878.0 1707.55  4883.0 1707.74  4911.5 1707.40
  4921.7 1707.56  4941.4 1707.04  4982.4 1707.04  5021.2 1706.63  5021.5 1706.13
  5025.0 1706.13  5025.2 1706.63  5043.7 1706.95  5064.2 1707.81  5105.2 1707.64
  5115.4 1708.04  5135.9 1708.06  5147.4 1708.52  5176.9 1708.77  5197.4 1709.46
  5239.3 1709.40  5248.7 1709.64  5277.5 1709.36  5282.6 1709.68  5303.0 1709.74
#Mann=3,-1,0
  4656.3   0.045       0  5021.2   0.045       0  5025.2   0.045       0
Bank Sta=5021.2,5025.2
Exp/Cntr=0.3,0.1

Type RM Length L Ch R = 1,958,170,170,170
BEGIN DESCRIPTION:
Elm 01 53 958.18
END DESCRIPTION:
XS GIS Cut Line= 3
      1565247.08      6860139.63      1565340.83      6859686.53
      1565423.28      6859392.78
#Sta/Elev= 30
  4535.5 1709.67  4578.0 1708.87  4608.6 1708.98  4646.5 1708.27  4669.9 1708.18
  4696.7 1707.53  4701.8 1707.71  4782.2 1706.67  4802.7 1706.90  4823.1 1706.62
  4842.2 1706.79  4847.3 1706.58  4904.8 1706.44  4976.3 1706.53  4984.5 1706.15
  4984.7 1705.65  4988.2 1705.65  4988.5 1706.15  4992.9 1706.51  4996.2 1706.15
  5111.1 1706.60  5131.7 1706.42  5173.2 1706.98  5184.5 1706.58  5194.0 1706.71
  5204.4 1706.44  5213.4 1706.61  5225.2 1706.35  5235.6 1706.70  5303.3 1706.26
#Mann=3,-1,0
  4535.5   0.045       0  4984.5   0.045       0  4988.5   0.045       0
Bank Sta=4984.5,4988.5
Exp/Cntr=0.3,0.1

Type RM Length L Ch R = 1,788,175,175,175
BEGIN DESCRIPTION:
Elm 01 53 771.54
END DESCRIPTION:
XS GIS Cut Line= 3
      1565415.48      6860130.96      1565481.82      6859711.28
      1565505.30      6859563.93
#Sta/Elev= 30
  4551.8 1708.13  4676.3 1705.74  4716.8 1705.55  4726.9 1704.67  4737.0 1704.90
  4767.4 1704.57  4777.7 1704.01  4782.7 1704.05  4828.2 1704.16  4840.1 1703.43
  4848.4 1703.88  4858.5 1703.43  4902.5 1703.49  4909.5 1703.22  4929.4 1703.50
  4949.6 1703.25  4959.8 1703.92  4964.9 1703.80  4968.0 1702.80  4968.3 1702.30
  4971.8 1702.30  4972.0 1702.80  4975.8 1703.52  5000.3 1703.52  5027.1 1704.81
  5061.0 1704.97  5071.1 1705.40  5091.4 1705.04  5111.7 1704.76  5125.9 1705.08
#Mann=6,-1,0
  4551.8   0.035       0  4782.7   0.045       0  4909.5    0.07       0
  4968.0    0.07       0  4972.0    0.07       0  5091.4   0.045       0
Bank Sta=4968,4972
Exp/Cntr=0.3,0.1

Type RM Length L Ch R = 1,613,87,87,87
BEGIN DESCRIPTION:
Elm 01 53 592.11
END DESCRIPTION:
XS GIS Cut Line= 3
      1565563.04      6860125.80      1565632.17      6859742.72
      1565554.04      6859612.30
#Sta/Elev= 30
  4656.4 1705.63  4715.1 1704.69  4745.6 1704.84  4776.1 1703.55  4796.4 1702.96
  4809.9 1703.13  4826.9 1702.39  4837.1 1702.72  4863.5 1702.26  4898.0 1702.32
  4908.2 1701.80  4917.1 1702.06  4948.9 1701.94  4969.2 1701.73  4980.8 1700.87
  4987.5 1700.84  4987.7 1700.34  4991.2 1700.34  4991.5 1700.84  4999.7 1701.89
  5020.0 1701.52  5062.8 1702.62  5084.6 1702.95  5090.4 1702.52  5097.8 1703.10
  5111.8 1702.93  5121.1 1703.35  5164.3 1703.72  5170.1 1704.27  5197.7 1704.01
#Mann=3,-1,0
  4656.4    0.07       0  4987.5    0.07       0  4991.5    0.07       0
Bank Sta=4987.5,4991.5
Exp/Cntr=0.3,0.1

Type RM Length L Ch R = 1,526,96,96,96
BEGIN DESCRIPTION:
Elm 01 53 518.55
END DESCRIPTION:
XS GIS Cut Line= 3
      1565678.59      6860264.81      1565699.80      6859778.64
      1565564.38      6859614.92
#Sta/Elev= 30
  4562.5 1704.43  4579.3 1704.78  4599.6 1704.20  4629.4 1704.17  4679.4 1703.45
  4709.5 1703.53  4789.5 1702.73  4809.5 1702.92  4824.4 1702.35  4839.6 1702.62
  4859.6 1701.91  4909.6 1701.54  4919.7 1701.15  4929.7 1701.47  4949.7 1700.67
  4989.7 1701.06  4997.7 1700.48  4998.0 1699.98  5001.5 1699.98  5001.7 1700.48
  5019.7 1701.73  5052.8 1701.28  5067.0 1701.68  5081.3 1701.52  5110.0 1702.52
  5124.3 1702.28  5128.2 1702.54  5138.6 1702.85  5210.4 1703.24  5261.6 1704.30
#Mann=5,-1,0
  4562.5    0.07       0  4997.7    0.07       0  5001.7    0.07       0
  5128.2   0.045       0  5210.4    0.07       0
Bank Sta=4997.7,5001.7
Exp/Cntr=0.3,0.1

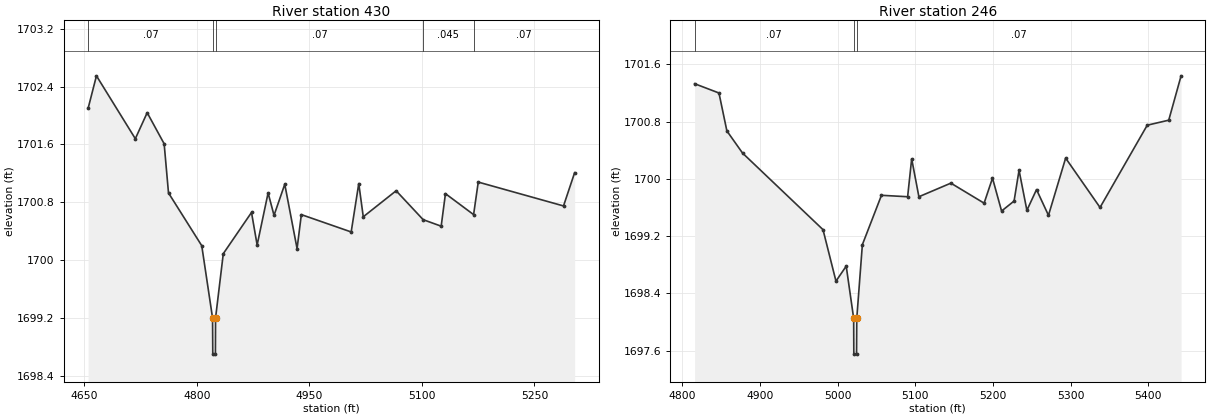
Type RM Length L Ch R = 1,430,184,184,184
BEGIN DESCRIPTION:
Elm 01 53 429.86
END DESCRIPTION:
XS GIS Cut Line= 3
      1565929.42      6860077.90      1565771.38      6859773.33
      1565626.28      6859504.98
#Sta/Elev= 30
  4655.3 1702.10  4666.4 1702.55  4718.2 1701.68  4734.0 1702.04  4756.6 1701.61
  4762.4 1700.93  4806.7 1700.20  4821.1 1699.20  4821.4 1698.70  4824.9 1698.70
  4825.1 1699.20  4835.4 1700.09  4873.0 1700.66  4880.5 1700.21  4895.1 1700.93
  4903.0 1700.62  4917.3 1701.05  4933.7 1700.16  4939.4 1700.63  5005.8 1700.39
  5015.9 1701.06  5021.9 1700.60  5065.7 1700.96  5101.7 1700.56  5125.7 1700.47
  5131.4 1700.92  5168.9 1700.63  5175.1 1701.08  5288.7 1700.75  5303.5 1701.21
#Mann=5,-1,0
  4655.3    0.07       0  4821.1    0.07       0  4825.1    0.07       0
  5101.7   0.045       0  5168.9    0.07       0
Bank Sta=4821.1,4825.1
Exp/Cntr=0.3,0.1

Type RM Length L Ch R = 1,246,0,0,0
BEGIN DESCRIPTION:
Elm 01 53 246.395
END DESCRIPTION:
XS GIS Cut Line= 4
      1565964.09      6859948.71      1565925.09      6859768.48
      1565885.91      6859631.58      1565619.66      6859493.76
#Sta/Elev= 30
  4815.6 1701.33  4847.0 1701.20  4857.2 1700.67  4877.4 1700.36  4981.0 1699.29
  4997.7 1698.57  5010.9 1698.78  5020.5 1698.05  5020.7 1697.55  5024.2 1697.55
  5024.5 1698.05  5031.7 1699.08  5056.3 1699.77  5090.0 1699.75  5095.2 1700.28
  5104.5 1699.75  5145.7 1699.94  5188.5 1699.66  5199.3 1700.01  5211.0 1699.55
  5227.1 1699.69  5233.5 1700.12  5243.6 1699.56  5256.0 1699.85  5271.4 1699.49
  5293.5 1700.29  5337.8 1699.60  5398.6 1700.75  5426.3 1700.82  5442.2 1701.44
#Mann=3,-1,0
  4815.6    0.07       0  5020.5    0.07       0  5024.5    0.07       0
Bank Sta=5020.5,5024.5
Exp/Cntr=0.3,0.1

Chan Stop Cuts=-1