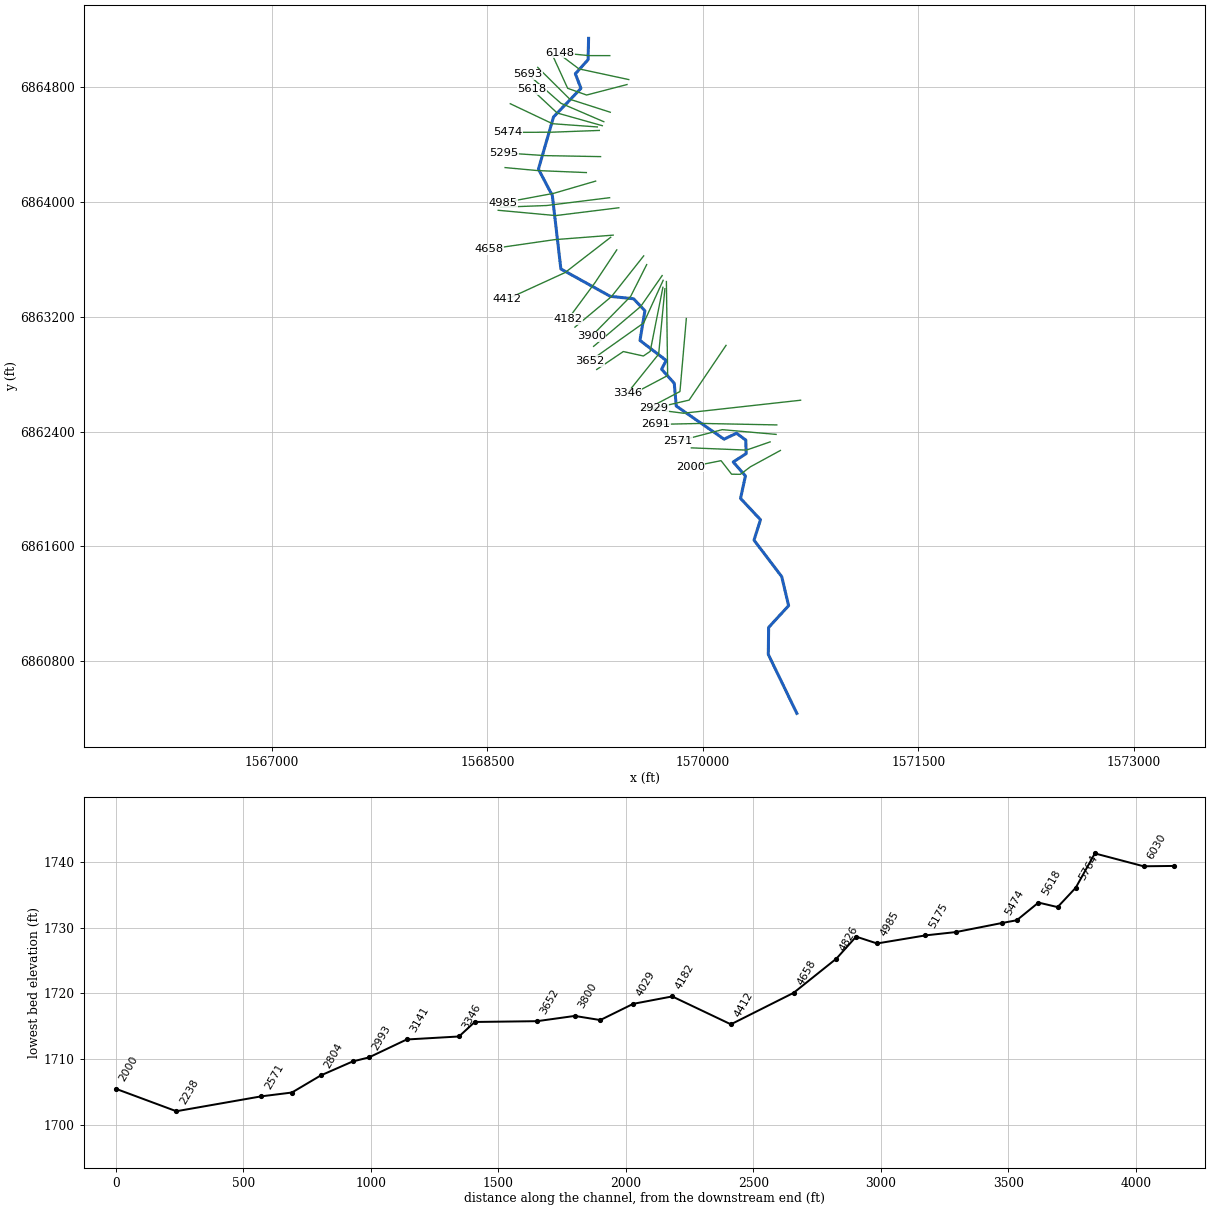
--- Elm 01 54.prj (project) ---

Proj Title=Elm 01 54 Base Level Engineering
Current Plan=p01
Default Exp/Contr=0.3,0.1
English Units
Geom File=g01
Flow File=f01
Plan File=p01
BEGIN DESCRIPTION:
Elm 01 54
END DESCRIPTION:

--- Elm 01 54.p01 (plan) ---

Plan Title=Multiple Run
Short Identifier=Multiple
Geom File=g01
Flow File=f01
Subcritical Flow
K Sum by GR= 0
Std Step Tol= 0.01
Critical Tol= 0.01
Num of Std Step Trials= 20
Max Error Tol= 0.3
Flow Tol Ratio= 0.001
Split Flow NTrial= 30
Split Flow Tol= 0.02
Split Flow Ratio= 0.02
Log Output Level= 0
Friction Slope Method= 1
Unsteady Friction Slope Method= 2
Unsteady Bridges Friction Slope Method= 1
Parabolic Critical Depth
Global Vel Dist=  1 , 1 , 1
Global Log Level= 0
CheckData=True
Encroach Param= -1, 0, 0, 0
BEGIN DESCRIPTION:
Multiple Run
END DESCRIPTION:

--- Elm 01 54.f01 (steady flow) ---

Flow Title=Multiple
Number of Profiles=7
Profile Names=10-year,25-year,50-year,1pct_min,100-year,1pct_plu,500-year
River Rch & RM= Elm 01 54,Reach-1,6148
     102     133     158     116     186     257     263
Boundary for River Rch & Prof#=Elm 01 54,Reach-1,1
Up Type=0
Dn Type=3
Dn Slope=0.005
Boundary for River Rch & Prof#=Elm 01 54,Reach-1,2
Up Type=0
Dn Type=3
Dn Slope=0.005
Boundary for River Rch & Prof#=Elm 01 54,Reach-1,3
Up Type=0
Dn Type=3
Dn Slope=0.005
Boundary for River Rch & Prof#=Elm 01 54,Reach-1,4
Up Type=0
Dn Type=3
Dn Slope=0.005
Boundary for River Rch & Prof#=Elm 01 54,Reach-1,5
Up Type=0
Dn Type=3
Dn Slope=0.005
Boundary for River Rch & Prof#=Elm 01 54,Reach-1,6
Up Type=0
Dn Type=3
Dn Slope=0.005
Boundary for River Rch & Prof#=Elm 01 54,Reach-1,7
Up Type=0
Dn Type=3
Dn Slope=0.005

--- Elm 01 54.g01 (geometry) ---

Geom Title=Existing Conditions

River Reach=Elm 01 54,Reach-1
Reach XY= 30
      1569205.00      6865138.00      1569201.48      6864989.45
      1569112.83      6864891.40      1569151.84      6864789.64
      1568960.70      6864590.38      1568855.76      6864227.31
      1568952.49      6864043.76      1569011.97      6863532.42
      1569356.47      6863341.56      1569518.37      6863324.63
      1569597.01      6863241.35      1569562.81      6863034.58
      1569745.81      6862894.95      1569713.02      6862834.68
      1569801.43      6862736.53      1569815.35      6862577.88
      1570148.28      6862347.17      1570234.96      6862388.37
      1570299.73      6862340.69      1570301.98      6862246.35
      1570212.04      6862188.20      1570296.99      6862091.33
      1570262.98      6861934.67      1570401.87      6861786.37
      1570356.80      6861644.11      1570549.53      6861390.45
      1570597.68      6861187.90      1570458.54      6861036.54
      1570456.20      6860848.50      1570655.00      6860438.00

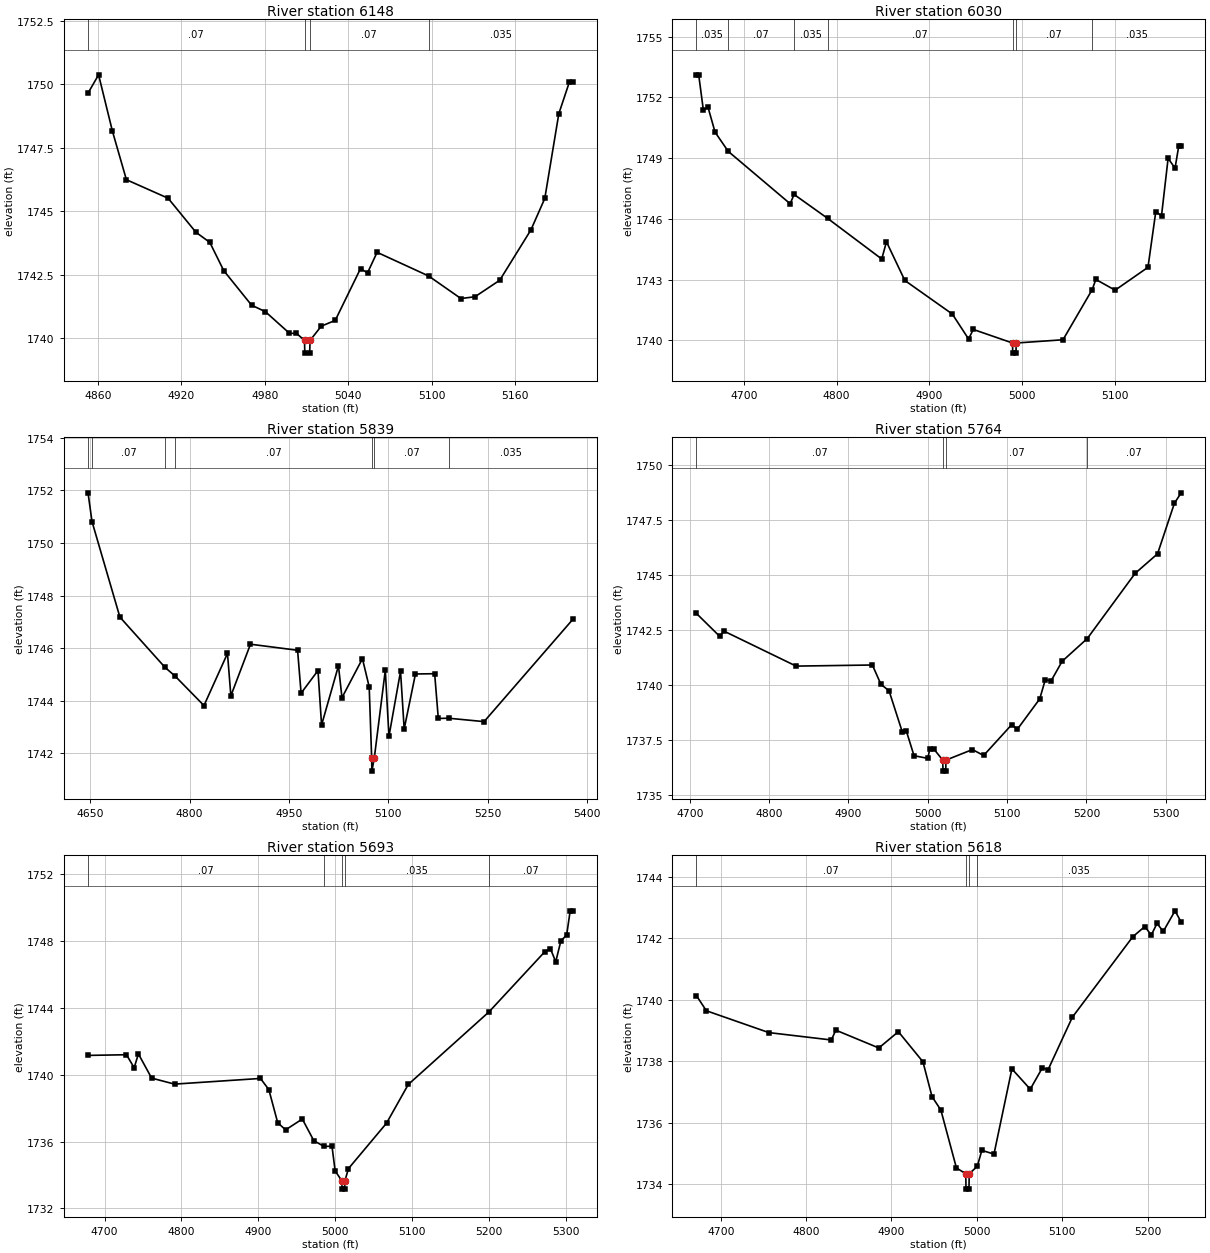
Type RM Length L Ch R = 1,6148,118,118,118
BEGIN DESCRIPTION:
Elm 01 54 6147.69
END DESCRIPTION:
XS GIS Cut Line= 3
      1569352.61      6865017.56      1569205.51      6865017.79
      1569005.03      6865038.00
#Sta/Elev= 30
  4852.9 1749.66  4860.5 1750.38  4870.5 1748.15  4880.5 1746.25  4910.5 1745.52
  4930.5 1744.18  4940.5 1743.78  4950.5 1742.67  4970.5 1741.31  4980.5 1741.05
  4997.8 1740.20  5002.8 1740.20  5008.6 1739.92  5008.8 1739.42  5012.3 1739.42
  5012.6 1739.92  5020.6 1740.48  5030.7 1740.71  5048.9 1742.75  5053.9 1742.58
  5060.8 1743.39  5097.8 1742.46  5121.1 1741.57  5131.2 1741.64  5149.0 1742.29
  5171.4 1744.27  5181.4 1745.51  5191.5 1748.85  5199.0 1750.08  5201.5 1750.08
#Mann=4,-1,0
  4852.9    0.07       0  5008.6    0.07       0  5012.6    0.07       0
  5097.8   0.035       0
Bank Sta=5008.6,5012.6
Exp/Cntr=0.3,0.1

Type RM Length L Ch R = 1,6030,191,191,191
BEGIN DESCRIPTION:
Elm 01 54 6030.473
END DESCRIPTION:
XS GIS Cut Line= 3
      1569484.60      6864850.89      1569137.34      6864925.55
      1569003.70      6865026.22
#Sta/Elev= 30
  4648.9 1753.12  4651.3 1753.12  4656.3 1751.38  4661.4 1751.51  4668.9 1750.29
  4683.1 1749.34  4749.9 1746.75  4754.1 1747.21  4790.2 1746.03  4848.6 1744.02
  4853.7 1744.87  4873.5 1742.96  4924.7 1741.30  4942.2 1740.07  4947.3 1740.54
  4989.6 1739.87  4989.8 1739.37  4993.3 1739.37  4993.6 1739.87  5044.0 1740.03
  5075.5 1742.51  5079.4 1743.01  5100.2 1742.48  5135.6 1743.61  5144.0 1746.35
  5150.2 1746.16  5157.3 1748.99  5164.8 1748.51  5168.8 1749.61  5171.4 1749.61
#Mann=7,-1,0
  4648.9   0.035       0  4683.1    0.07       0  4754.1   0.035       0
  4790.2    0.07       0  4989.6    0.07       0  4993.6    0.07       0
  5075.5   0.035       0
Bank Sta=4989.6,4993.6
Exp/Cntr=0.3,0.1

Type RM Length L Ch R = 1,5839,75,75,75
BEGIN DESCRIPTION:
Elm 01 54 5838.585
END DESCRIPTION:
XS GIS Cut Line= 4
      1569472.38      6864816.16      1569191.16      6864743.26
      1569059.22      6864790.13      1568934.02      6865063.93
#Sta/Elev= 30
  4646.6 1751.90  4652.6 1750.81  4694.7 1747.18  4762.8 1745.27  4778.0 1744.94
  4821.6 1743.82  4857.1 1745.80  4862.2 1744.19  4891.8 1746.15  4962.9 1745.92
  4968.2 1744.29  4993.7 1745.15  4999.1 1743.08  5024.6 1745.33  5029.9 1744.12
  5060.8 1745.60  5071.0 1744.53  5074.7 1741.83  5075.0 1741.33  5078.7 1741.83
  5095.3 1745.16  5100.8 1742.65  5118.3 1745.12  5123.8 1742.93  5140.8 1745.02
  5169.8 1745.03  5175.3 1743.33  5190.7 1743.34  5244.4 1743.21  5378.2 1747.09
#Mann=7,-1,0
  4646.6   0.035       0  4652.6    0.07       0  4762.8   0.035       0
  4778.0    0.07       0  5074.7    0.07       0  5078.7    0.07       0
  5190.7   0.035       0
Bank Sta=5074.7,5078.7
Exp/Cntr=0.3,0.1

Type RM Length L Ch R = 1,5764,71,71,71
BEGIN DESCRIPTION:
Elm 01 54 5764.249
END DESCRIPTION:
XS GIS Cut Line= 3
      1569356.09      6864623.47      1569074.84      6864713.74
      1568850.87      6864935.98
#Sta/Elev= 30
  4708.5 1743.26  4737.8 1742.22  4743.1 1742.46  4834.1 1740.87  4930.2 1740.92
  4941.0 1740.04  4951.2 1739.75  4967.8 1737.89  4973.1 1737.91  4982.7 1736.80
  5000.0 1736.68  5002.7 1737.12  5007.3 1737.12  5018.9 1736.60  5019.2 1736.10
  5022.7 1736.10  5022.9 1736.60  5056.3 1737.08  5070.4 1736.81  5105.8 1738.21
  5112.9 1738.00  5141.1 1739.38  5148.2 1740.26  5155.3 1740.19  5169.4 1741.09
  5201.0 1742.12  5261.3 1745.08  5289.6 1745.97  5310.9 1748.27  5319.4 1748.74
#Mann=4,-1,0
  4708.5    0.07       0  5018.9    0.07       0  5022.9    0.07       0
  5201.0    0.07       0
Bank Sta=5018.9,5022.9
Exp/Cntr=0.3,0.1

Type RM Length L Ch R = 1,5693,75,75,75
BEGIN DESCRIPTION:
Elm 01 54 5693.075
END DESCRIPTION:
XS GIS Cut Line= 3
      1569310.97      6864557.49      1569012.34      6864685.97
      1568783.15      6864887.38
#Sta/Elev= 30
  4678.5 1741.16  4728.5 1741.20  4738.5 1740.42  4744.0 1741.25  4761.2 1739.80
  4791.0 1739.44  4902.7 1739.78  4913.6 1739.11  4925.1 1737.13  4935.4 1736.70
  4957.1 1737.35  4972.1 1736.05  4985.3 1735.71  4995.7 1735.72  4999.8 1734.24
  5008.5 1733.65  5008.7 1733.15  5012.2 1733.15  5012.5 1733.65  5017.1 1734.38
  5066.6 1737.10  5094.9 1739.42  5199.9 1743.77  5272.4 1747.37  5279.6 1747.56
  5286.6 1746.77  5293.3 1748.02  5300.8 1748.37  5305.4 1749.82  5308.7 1749.82
#Mann=5,-1,0
  4678.5    0.07       0  4985.3   0.035       0  5008.5   0.035       0
  5012.5   0.035       0  5199.9    0.07       0
Bank Sta=5008.5,5012.5
Exp/Cntr=0.3,0.1

Type RM Length L Ch R = 1,5618,85,85,85
BEGIN DESCRIPTION:
Elm 01 54 5618.258
END DESCRIPTION:
XS GIS Cut Line= 3
      1569300.58      6864529.71      1568986.30      6864618.26
      1568809.73      6864782.71
#Sta/Elev= 30
  4671.6 1740.13  4683.2 1739.64  4756.4 1738.93  4829.6 1738.69  4834.8 1739.01
  4885.2 1738.43  4908.1 1738.96  4936.9 1737.98  4947.5 1736.85  4957.9 1736.41
  4976.1 1734.53  4987.1 1734.34  4987.3 1733.84  4990.8 1733.84  4991.1 1734.34
  5000.5 1734.58  5005.9 1735.10  5020.1 1734.98  5041.1 1737.75  5062.6 1737.09
  5076.7 1737.78  5083.6 1737.73  5111.9 1739.43  5182.8 1742.05  5196.9 1742.38
  5204.3 1742.10  5211.1 1742.48  5218.4 1742.22  5232.2 1742.89  5239.4 1742.52
#Mann=4,-1,0
  4671.6    0.07       0  4987.1    0.07       0  4991.1    0.07       0
  5000.5   0.035       0
Bank Sta=4987.1,4991.1
Exp/Cntr=0.3,0.1

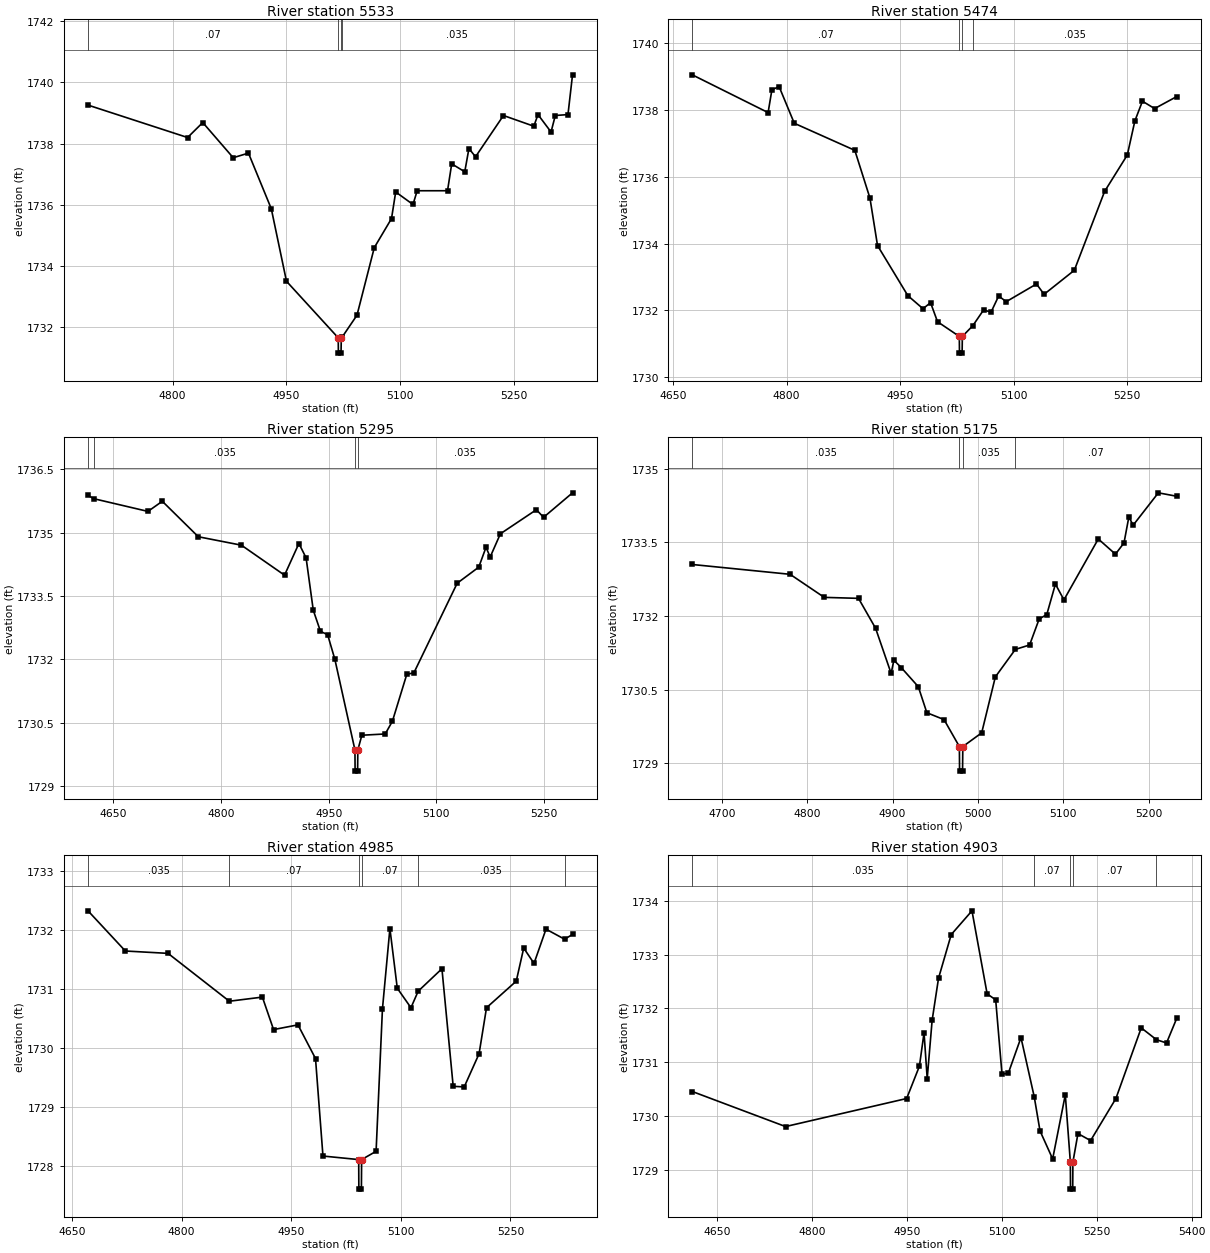
Type RM Length L Ch R = 1,5533,59,59,59
BEGIN DESCRIPTION:
Elm 01 54 5532.744
END DESCRIPTION:
XS GIS Cut Line= 3
      1569265.83      6864521.03      1568953.32      6864543.60
      1568659.53      6864682.76
#Sta/Elev= 30
  4688.5 1739.26  4819.7 1738.20  4839.7 1738.69  4879.8 1737.54  4899.9 1737.69
  4930.0 1735.87  4950.0 1733.50  5018.2 1731.65  5018.4 1731.15  5021.9 1731.15
  5022.2 1731.65  5023.5 1731.68  5042.9 1732.39  5065.7 1734.60  5088.4 1735.55
  5093.9 1736.42  5116.7 1736.01  5122.2 1736.46  5162.2 1736.46  5167.7 1737.34
  5184.9 1737.08  5190.4 1737.84  5199.1 1737.57  5235.9 1738.92  5275.9 1738.57
  5281.4 1738.95  5298.6 1738.38  5304.2 1738.92  5320.9 1738.95  5326.9 1740.25
#Mann=4,-1,0
  4688.5    0.07       0  5018.2    0.07       0  5022.2    0.07       0
  5023.5   0.035       0
Bank Sta=5018.2,5022.2
Exp/Cntr=0.3,0.1

Type RM Length L Ch R = 1,5474,179,179,179
BEGIN DESCRIPTION:
Elm 01 54 5473.984
END DESCRIPTION:
XS GIS Cut Line= 3
      1569279.66      6864496.73      1568951.58      6864484.58
      1568639.59      6864482.84
#Sta/Elev= 30
  4675.4 1739.05  4775.6 1737.92  4780.6 1738.60  4790.1 1738.70  4810.2 1737.60
  4890.2 1736.79  4910.2 1735.36  4920.2 1733.94  4960.3 1732.44  4980.3 1732.05
  4990.3 1732.23  4999.5 1731.66  5028.3 1731.22  5028.5 1730.72  5032.0 1730.72
  5032.3 1731.22  5046.1 1731.54  5060.3 1732.01  5070.3 1731.95  5080.3 1732.43
  5090.3 1732.26  5130.3 1732.79  5140.3 1732.48  5180.3 1733.20  5220.3 1735.56
  5250.3 1736.65  5260.3 1737.67  5270.3 1738.26  5286.4 1738.04  5315.7 1738.40
#Mann=4,-1,0
  4675.4    0.07       0  5028.3    0.07       0  5032.3    0.07       0
  5046.1   0.035       0
Bank Sta=5028.3,5032.3
Exp/Cntr=0.3,0.1

Type RM Length L Ch R = 1,5295,120,120,120
BEGIN DESCRIPTION:
Elm 01 54 5295.129
END DESCRIPTION:
XS GIS Cut Line= 3
      1569288.43      6864314.44      1568904.71      6864321.38
      1568614.82      6864340.48
#Sta/Elev= 30
  4615.1 1735.88  4623.4 1735.80  4698.5 1735.50  4718.5 1735.74  4768.6 1734.90
  4828.6 1734.70  4888.6 1733.99  4908.6 1734.74  4918.6 1734.40  4928.6 1733.16
  4938.6 1732.66  4948.6 1732.58  4958.6 1732.00  4986.6 1729.85  4986.8 1729.35
  4990.3 1729.35  4990.6 1729.85  4996.2 1730.20  5028.7 1730.23  5038.7 1730.53
  5058.7 1731.64  5068.7 1731.68  5128.9 1733.80  5158.9 1734.18  5169.0 1734.65
  5174.8 1734.42  5189.0 1734.97  5239.1 1735.54  5249.1 1735.36  5289.4 1735.94
#Mann=4,-1,0
  4615.1    0.07       0  4623.4   0.035       0  4986.6   0.035       0
  4990.6   0.035       0
Bank Sta=4986.6,4990.6
Exp/Cntr=0.3,0.1

Type RM Length L Ch R = 1,5175,190,190,190
BEGIN DESCRIPTION:
Elm 01 54 5174.988
END DESCRIPTION:
XS GIS Cut Line= 3
      1569189.41      6864203.33      1568850.89      6864217.22
      1568623.45      6864238.05
#Sta/Elev= 30
  4665.5 1733.05  4780.0 1732.85  4820.0 1732.38  4860.1 1732.36  4880.1 1731.75
  4898.3 1730.83  4901.5 1731.10  4910.1 1730.95  4930.1 1730.56  4940.1 1730.03
  4960.2 1729.89  4978.2 1729.34  4978.4 1728.84  4981.9 1728.84  4982.2 1729.34
  5004.3 1729.62  5020.3 1730.76  5043.7 1731.32  5060.4 1731.41  5071.6 1731.94
  5080.5 1732.03  5090.6 1732.65  5100.6 1732.33  5140.8 1733.57  5160.9 1733.26
  5170.9 1733.49  5176.6 1734.02  5181.6 1733.85  5211.1 1734.51  5232.7 1734.44
#Mann=4,-1,0
  4665.5   0.035       0  4978.2   0.035       0  4982.2   0.035       0
  5043.7    0.07       0
Bank Sta=4978.2,4982.2
Exp/Cntr=0.3,0.1

Type RM Length L Ch R = 1,4985,82,82,82
BEGIN DESCRIPTION:
Elm 01 54 4992.123
END DESCRIPTION:
XS GIS Cut Line= 3
      1569254.05      6864143.98      1568962.37      6864058.90
      1568609.28      6863993.13
#Sta/Elev= 30
  4672.0 1732.32  4723.1 1731.64  4781.5 1731.60  4865.4 1730.79  4910.6 1730.86
  4925.9 1730.31  4959.3 1730.39  4983.3 1729.82  4993.5 1728.17  5042.4 1728.11
  5042.6 1727.61  5046.1 1727.61  5046.4 1728.11  5066.2 1728.25  5074.9 1730.66
  5085.1 1732.02  5095.2 1731.01  5113.9 1730.68  5123.8 1730.96  5156.3 1731.34
  5171.7 1729.35  5186.8 1729.34  5207.1 1729.90  5217.3 1730.68  5258.0 1731.13
  5268.2 1731.69  5282.3 1731.43  5298.7 1732.01  5324.1 1731.84  5335.0 1731.92
#Mann=6,-1,0
  4672.0   0.035       0  4865.4    0.07       0  5042.4    0.07       0
  5046.4    0.07       0  5123.8   0.035       0  5324.1   0.045       0
Bank Sta=5042.4,5046.4
Exp/Cntr=0.3,0.1

Type RM Length L Ch R = 1,4903,77,77,77
BEGIN DESCRIPTION:
Elm 01 54 10.0
END DESCRIPTION:
XS GIS Cut Line= 3
      1569351.42      6864028.39      1568912.48      6863973.96
      1568588.82      6863961.76
#Sta/Elev= 30
  4610.3 1730.46  4757.8 1729.81  4949.3 1730.33  4969.5 1730.93  4976.8 1731.55
  4981.8 1730.70  4989.6 1731.78  4999.7 1732.56  5019.8 1733.37  5052.6 1733.81
  5076.6 1732.27  5090.1 1732.16  5100.1 1730.78  5110.1 1730.80  5130.1 1731.46
  5151.1 1730.36  5160.2 1729.73  5180.2 1729.21  5200.2 1730.40  5208.2 1729.15
  5208.4 1728.65  5211.9 1728.65  5212.2 1729.15  5220.2 1729.68  5240.2 1729.55
  5280.2 1730.33  5320.3 1731.64  5344.4 1731.42  5360.3 1731.36  5376.5 1731.82
#Mann=5,-1,0
  4610.3   0.035       0  5151.1    0.07       0  5208.2   0.035       0
  5212.2    0.07       0  5344.4   0.045       0
Bank Sta=5208.2,5212.2
Exp/Cntr=0.3,0.1

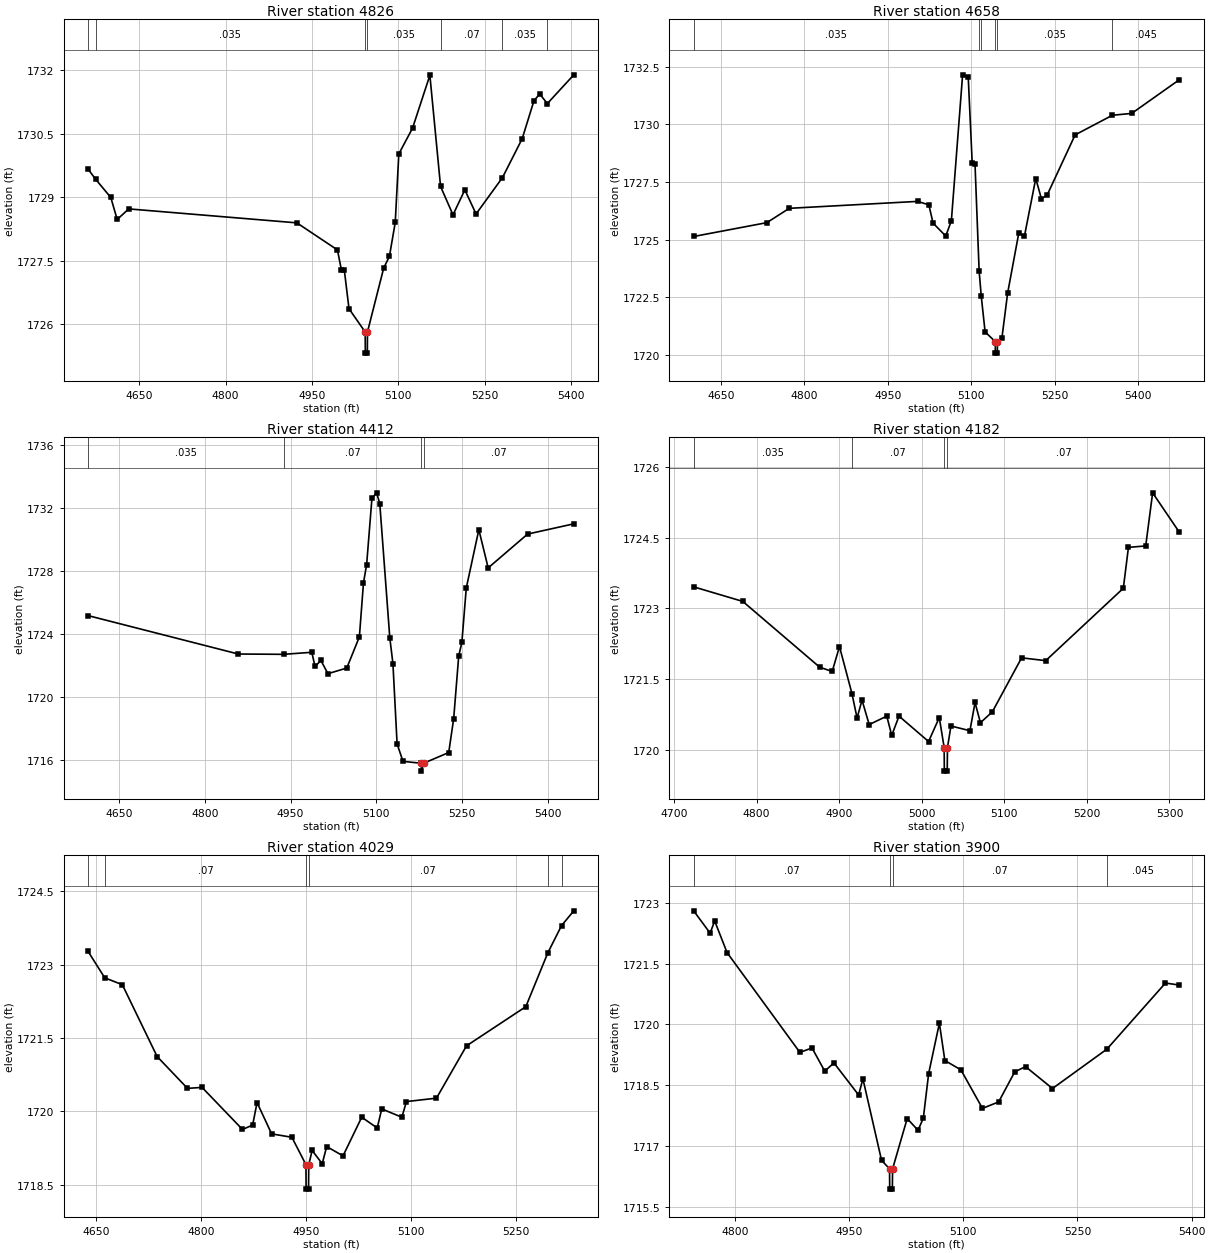
Type RM Length L Ch R = 1,4826,168,168,168
BEGIN DESCRIPTION:
Elm 01 54 4825.865
END DESCRIPTION:
XS GIS Cut Line= 3
      1569415.21      6863958.35      1568976.18      6863903.91
      1568575.86      6863940.78
#Sta/Elev= 30
  4560.8 1729.66  4574.0 1729.42  4600.3 1728.99  4611.4 1728.47  4631.5 1728.72
  4923.8 1728.39  4994.3 1727.75  5001.3 1727.27  5006.3 1727.27  5014.4 1726.36
  5042.5 1725.81  5042.8 1725.31  5046.3 1725.31  5046.5 1725.81  5074.7 1727.32
  5084.7 1727.60  5094.8 1728.40  5101.0 1730.02  5124.9 1730.63  5155.0 1731.88
  5173.6 1729.25  5195.2 1728.58  5215.8 1729.17  5235.3 1728.60  5281.2 1729.46
  5315.5 1730.38  5335.8 1731.27  5345.8 1731.44  5359.2 1731.21  5405.2 1731.89
#Mann=7,-1,0
  4560.8    0.07       0  4574.0   0.035       0  5042.5   0.035       0
  5046.5   0.035       0  5173.6    0.07       0  5281.2   0.035       0
  5359.2   0.045       0
Bank Sta=5042.5,5046.5
Exp/Cntr=0.3,0.1

Type RM Length L Ch R = 1,4658,246,246,246
BEGIN DESCRIPTION:
Elm 01 54 4713.063
END DESCRIPTION:
XS GIS Cut Line= 3
      1569376.14      6863767.76      1568967.00      6863736.15
      1568509.60      6863670.14
#Sta/Elev= 30
  4601.1 1725.14  4732.6 1725.74  4772.8 1726.36  5003.4 1726.66  5023.6 1726.51
  5031.1 1725.72  5053.9 1725.16  5064.0 1725.82  5084.2 1732.14  5094.3 1732.04
  5101.4 1728.34  5106.5 1728.26  5113.9 1723.64  5117.7 1722.55  5124.6 1721.01
  5142.8 1720.59  5143.1 1720.09  5146.6 1720.09  5146.8 1720.59  5154.9 1720.76
  5165.0 1722.68  5185.2 1725.30  5195.3 1725.16  5215.6 1727.65  5225.7 1726.78
  5235.8 1726.92  5286.3 1729.54  5353.3 1730.39  5388.0 1730.47  5473.6 1731.93
#Mann=6,-1,0
  4601.1   0.035       0  5113.9    0.07       0  5117.7   0.035       0
  5142.8   0.035       0  5146.8   0.035       0  5353.3   0.045       0
Bank Sta=5142.8,5146.8
Exp/Cntr=0.3,0.1

Type RM Length L Ch R = 1,4412,230,230,230
BEGIN DESCRIPTION:
Elm 01 54 4410.2
END DESCRIPTION:
XS GIS Cut Line= 3
      1569358.99      6863752.90      1569041.15      6863507.06
      1568633.97      6863320.51
#Sta/Elev= 30
  4595.7 1725.17  4858.5 1722.73  4937.8 1722.71  4987.1 1722.84  4992.7 1721.94
  5003.0 1722.32  5015.3 1721.48  5048.3 1721.84  5070.3 1723.82  5077.5 1727.26
  5083.0 1728.41  5092.3 1732.63  5100.5 1732.97  5106.0 1732.28  5123.5 1723.77
  5129.0 1722.12  5136.3 1717.02  5146.6 1715.91  5178.6 1715.79  5178.8 1715.29
  5182.6 1715.79  5226.6 1716.47  5235.3 1718.63  5244.1 1722.61  5249.6 1723.47
  5257.3 1726.92  5279.3 1730.63  5295.6 1728.20  5364.6 1730.35  5445.4 1731.00
#Mann=4,-1,0
  4595.7   0.035       0  4937.8    0.07       0  5178.6    0.07       0
  5182.6    0.07       0
Bank Sta=5178.6,5182.6
Exp/Cntr=0.3,0.1

Type RM Length L Ch R = 1,4182,153,153,153
BEGIN DESCRIPTION:
Elm 01 54 4181.87
END DESCRIPTION:
XS GIS Cut Line= 3
      1569401.24      6863665.14      1569250.19      6863437.70
      1569062.70      6863184.24
#Sta/Elev= 30
  4723.7 1723.46  4783.2 1723.15  4876.4 1721.75  4891.5 1721.66  4900.3 1722.19
  4915.4 1721.19  4921.6 1720.67  4927.6 1721.05  4936.3 1720.53  4957.6 1720.71
  4963.6 1720.30  4972.4 1720.71  5008.2 1720.17  5021.2 1720.68  5027.1 1720.04
  5027.3 1719.54  5030.8 1719.54  5031.1 1720.04  5035.3 1720.50  5058.3 1720.40
  5064.5 1721.00  5071.0 1720.57  5085.4 1720.80  5120.9 1721.95  5150.1 1721.89
  5244.1 1723.43  5250.3 1724.30  5271.2 1724.33  5279.6 1725.46  5312.0 1724.62
#Mann=4,-1,0
  4723.7   0.035       0  4915.4    0.07       0  5027.1    0.07       0
  5031.1    0.07       0
Bank Sta=5027.1,5031.1
Exp/Cntr=0.3,0.1

Type RM Length L Ch R = 1,4029,129,129,129
BEGIN DESCRIPTION:
Elm 01 54 4029.42
END DESCRIPTION:
XS GIS Cut Line= 3
      1569588.70      6863623.43      1569364.78      6863340.48
      1569109.80      6863127.13
#Sta/Elev= 30
  4638.8 1723.27  4662.6 1722.73  4687.7 1722.59  4737.4 1721.12  4780.7 1720.47
  4801.5 1720.49  4859.2 1719.63  4873.7 1719.72  4880.0 1720.18  4900.8 1719.54
  4929.7 1719.47  4949.8 1718.91  4950.0 1718.41  4953.5 1718.41  4953.8 1718.91
  4958.6 1719.20  4973.0 1718.93  4979.4 1719.28  5002.7 1719.09  5029.4 1719.88
  5051.5 1719.66  5058.0 1720.05  5086.7 1719.88  5093.2 1720.20  5136.1 1720.27
  5179.0 1721.34  5263.6 1722.14  5295.0 1723.24  5314.7 1723.80  5332.1 1724.10
#Mann=6,-1,0
  4638.8   0.035       0  4662.6    0.07       0  4949.8    0.07       0
  4953.8    0.07       0  5295.0   0.045       0  5314.7    0.07       0
Bank Sta=4949.8,4953.8
Exp/Cntr=0.3,0.1

Type RM Length L Ch R = 1,3900,100,100,100
BEGIN DESCRIPTION:
Elm 01 54 3900.45
END DESCRIPTION:
XS GIS Cut Line= 3
      1569609.55      6863562.67      1569498.46      6863342.22
      1569224.28      6863062.84
#Sta/Elev= 30
  4745.6 1722.80  4767.2 1722.25  4773.2 1722.55  4789.5 1721.77  4885.2 1719.31
  4901.1 1719.42  4917.8 1718.85  4930.0 1719.05  4962.4 1718.26  4968.0 1718.66
  4992.5 1716.65  5003.0 1716.44  5003.2 1715.94  5006.7 1715.94  5007.0 1716.44
  5026.2 1717.68  5040.4 1717.39  5047.4 1717.69  5054.4 1718.79  5068.5 1720.03
  5075.7 1719.11  5096.8 1718.88  5125.1 1717.93  5146.4 1718.09  5167.5 1718.83
  5181.7 1718.96  5217.1 1718.42  5288.6 1719.39  5365.6 1721.02  5383.9 1720.97
#Mann=4,-1,0
  4745.6    0.07       0  5003.0    0.07       0  5007.0    0.07       0
  5288.6   0.045       0
Bank Sta=5003,5007
Exp/Cntr=0.3,0.1

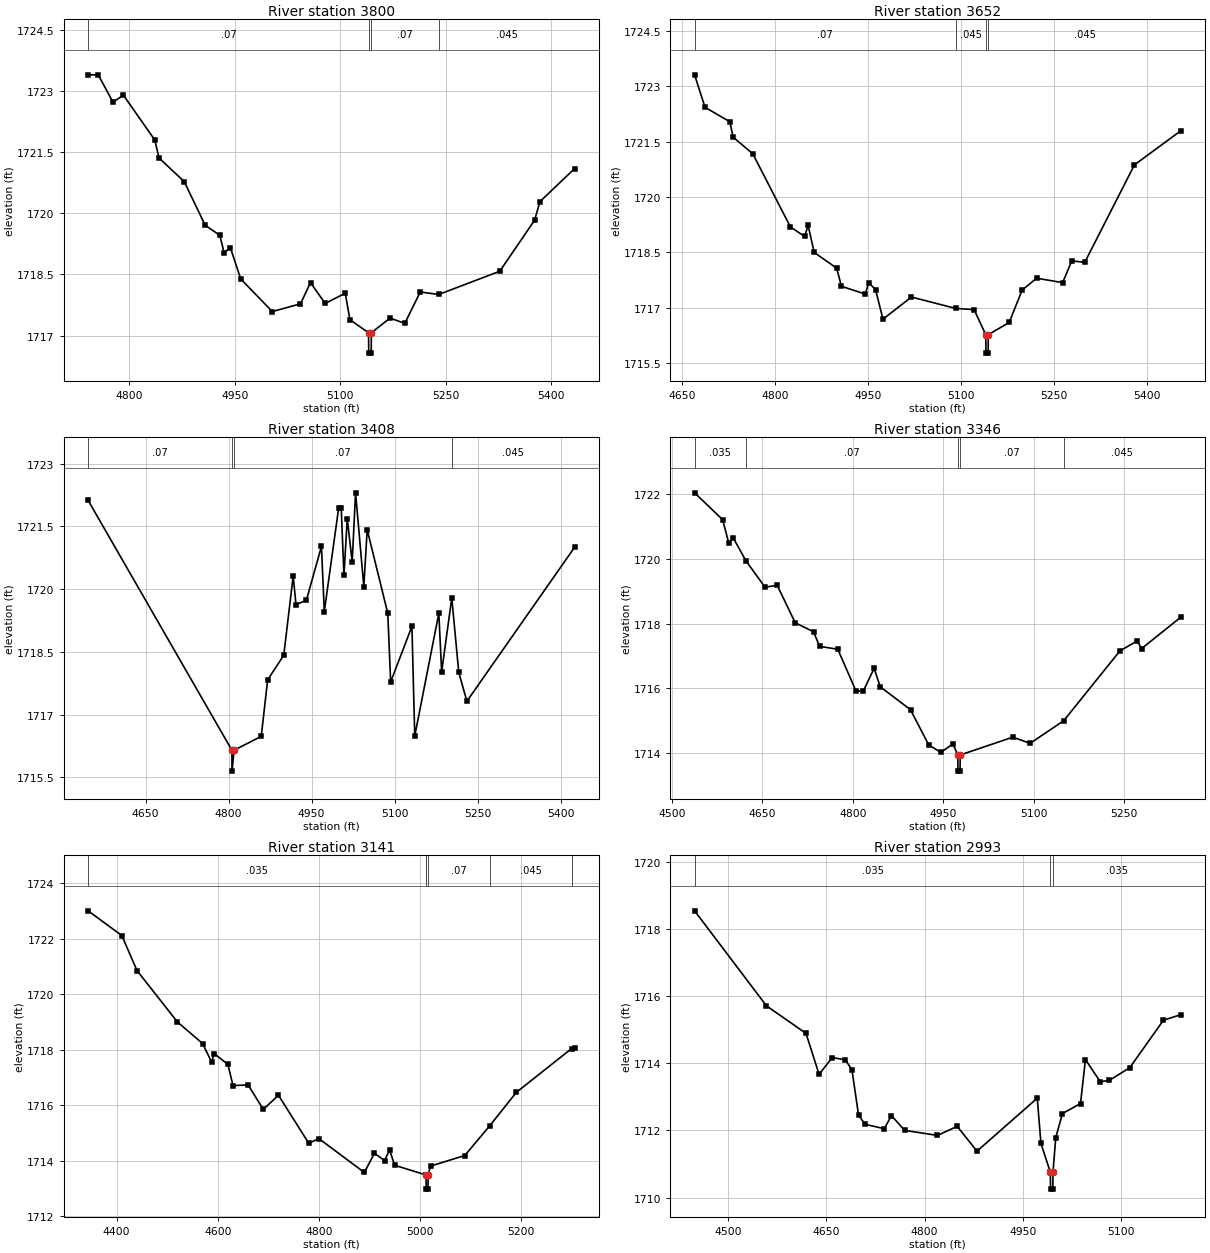
Type RM Length L Ch R = 1,3800,148,148,148
BEGIN DESCRIPTION:
Elm 01 54 3799.71
END DESCRIPTION:
XS GIS Cut Line= 3
      1569717.18      6863486.27      1569567.90      6863271.04
      1569239.89      6862993.36
#Sta/Elev= 30
  4741.5 1723.40  4755.9 1723.40  4776.8 1722.73  4791.7 1722.90  4836.3 1721.80
  4842.3 1721.36  4878.1 1720.78  4907.9 1719.71  4928.8 1719.46  4934.9 1719.03
  4943.7 1719.16  4958.5 1718.39  5003.4 1717.59  5043.4 1717.78  5057.7 1718.30
  5078.5 1717.79  5107.1 1718.04  5113.7 1717.39  5140.2 1717.07  5140.5 1716.57
  5144.0 1716.57  5144.2 1717.07  5170.8 1717.43  5191.7 1717.30  5213.7 1718.07
  5240.1 1718.01  5326.8 1718.58  5376.2 1719.83  5384.0 1720.29  5433.2 1721.10
#Mann=4,-1,0
  4741.5    0.07       0  5140.2    0.07       0  5144.2    0.07       0
  5240.1   0.045       0
Bank Sta=5140.2,5144.2
Exp/Cntr=0.3,0.1

Type RM Length L Ch R = 1,3652,244,244,244
BEGIN DESCRIPTION:
Elm 01 54 3651.66
END DESCRIPTION:
XS GIS Cut Line= 3
      1569724.14      6863453.30      1569588.73      6863156.45
      1569215.29      6862891.93
#Sta/Elev= 30
  4670.5 1723.31  4687.3 1722.43  4727.2 1722.04  4732.7 1721.62  4764.3 1721.17
  4824.9 1719.19  4847.9 1718.93  4853.4 1719.23  4863.2 1718.50  4899.5 1718.07
  4907.1 1717.58  4945.6 1717.37  4951.1 1717.68  4962.1 1717.49  4974.1 1716.69
  5019.9 1717.29  5091.4 1716.98  5120.8 1716.95  5139.7 1716.27  5140.0 1715.77
  5143.5 1715.77  5143.7 1716.27  5177.4 1716.60  5198.3 1717.48  5221.7 1717.80
  5263.5 1717.68  5278.3 1718.27  5299.2 1718.23  5379.2 1720.87  5454.4 1721.80
#Mann=4,-1,0
  4670.5    0.07       0  5091.4   0.045       0  5139.7    0.07       0
  5143.7   0.045       0
Bank Sta=5139.7,5143.7
Exp/Cntr=0.3,0.1

Type RM Length L Ch R = 1,3408,62,62,62
BEGIN DESCRIPTION:
Elm 01 54 3408.44
END DESCRIPTION:
XS GIS Cut Line= 5
      1569722.41      6863404.68      1569633.87      6862958.54
      1569586.43      6862926.24      1569446.86      6862957.28
      1569261.53      6862832.20
#Sta/Elev= 30
  4546.3 1722.12  4806.0 1716.15  4806.2 1715.65  4810.0 1716.15  4859.0 1716.48
  4870.6 1717.83  4899.7 1718.42  4916.7 1720.31  4921.8 1719.63  4940.5 1719.73
  4967.8 1721.02  4972.9 1719.46  4998.9 1721.94  5003.5 1721.94  5008.4 1720.33
  5014.4 1721.68  5023.3 1720.65  5029.4 1722.30  5044.3 1720.06  5050.4 1721.42
  5087.6 1719.42  5092.8 1717.78  5131.2 1719.11  5136.3 1716.49  5179.8 1719.42
  5184.9 1718.02  5203.2 1719.79  5215.8 1718.01  5230.5 1717.32  5425.1 1721.00
#Mann=4,-1,0
  4546.3    0.07       0  4806.0    0.07       0  4810.0    0.07       0
  5203.2   0.045       0
Bank Sta=4806,4810
Exp/Cntr=0.3,0.1

Type RM Length L Ch R = 1,3346,205,205,205
BEGIN DESCRIPTION:
Elm 01 54 3345.98
END DESCRIPTION:
XS GIS Cut Line= 3
      1569736.30      6863394.30      1569692.90      6862939.44
      1569474.17      6862666.89
#Sta/Elev= 30
  4537.9 1722.05  4584.4 1721.22  4594.5 1720.50  4601.9 1720.66  4622.9 1719.95
  4654.7 1719.13  4674.8 1719.19  4704.7 1718.03  4735.1 1717.75  4745.1 1717.30
  4775.3 1717.21  4805.4 1715.92  4817.6 1715.92  4835.5 1716.62  4845.6 1716.05
  4895.8 1715.34  4926.0 1714.25  4946.0 1714.02  4966.1 1714.28  4974.2 1713.94
  4974.4 1713.44  4977.9 1713.44  4978.2 1713.94  5065.3 1714.49  5094.1 1714.30
  5149.8 1715.00  5242.9 1717.16  5271.7 1717.47  5278.8 1717.23  5344.3 1718.21
#Mann=5,-1,0
  4537.9   0.035       0  4622.9    0.07       0  4974.2    0.07       0
  4978.2    0.07       0  5149.8   0.045       0
Bank Sta=4974.2,4978.2
Exp/Cntr=0.3,0.1

Type RM Length L Ch R = 1,3141,148,148,148
BEGIN DESCRIPTION:
Elm 01 54 3141.41
END DESCRIPTION:
XS GIS Cut Line= 3
      1569746.72      6863444.65      1569755.40      6862790.13
      1569482.82      6862646.03
#Sta/Elev= 30
  4343.5 1723.00  4410.2 1722.11  4440.2 1720.85  4520.2 1719.00  4570.2 1718.22
  4588.0 1717.55  4593.0 1717.86  4620.2 1717.47  4630.2 1716.71  4660.2 1716.73
  4690.2 1715.85  4720.2 1716.36  4780.2 1714.63  4800.2 1714.80  4890.2 1713.58
  4910.2 1714.27  4930.2 1714.01  4940.2 1714.39  4950.2 1713.84  5012.1 1713.49
  5012.4 1713.48  5012.7 1712.98  5016.2 1712.98  5016.4 1713.48  5021.2 1713.81
  5089.0 1714.19  5138.8 1715.27  5190.8 1716.46  5300.3 1718.04  5306.4 1718.06
#Mann=6,-1,0
  4343.5   0.035       0  5012.1    0.07       0  5012.4   0.035       0
  5016.4    0.07       0  5138.8   0.045       0  5300.3   0.035       0
Bank Sta=5012.4,5016.4
Exp/Cntr=0.3,0.1

Type RM Length L Ch R = 1,2993,64,64,64
BEGIN DESCRIPTION:
Elm 01 54 2992.07
END DESCRIPTION:
XS GIS Cut Line= 3
      1569885.53      6863187.33      1569841.12      6862678.86
      1569635.83      6862570.58
#Sta/Elev= 30
  4449.1 1718.54  4558.8 1715.71  4619.1 1714.89  4639.1 1713.67  4659.2 1714.17
  4679.3 1714.10  4689.3 1713.80  4699.4 1712.45  4709.4 1712.18  4738.5 1712.05
  4749.6 1712.44  4769.6 1712.00  4819.8 1711.85  4849.9 1712.12  4880.1 1711.38
  4972.1 1712.96  4977.7 1711.61  4992.1 1710.75  4992.3 1710.25  4995.8 1710.25
  4996.1 1710.75  5000.3 1711.78  5010.5 1712.50  5038.1 1712.80  5045.6 1714.11
  5068.2 1713.45  5082.2 1713.49  5113.4 1713.87  5164.6 1715.28  5191.6 1715.45
#Mann=3,-1,0
  4449.1   0.035       0  4992.1   0.035       0  4996.1   0.035       0
Bank Sta=4992.1,4996.1
Exp/Cntr=0.3,0.1

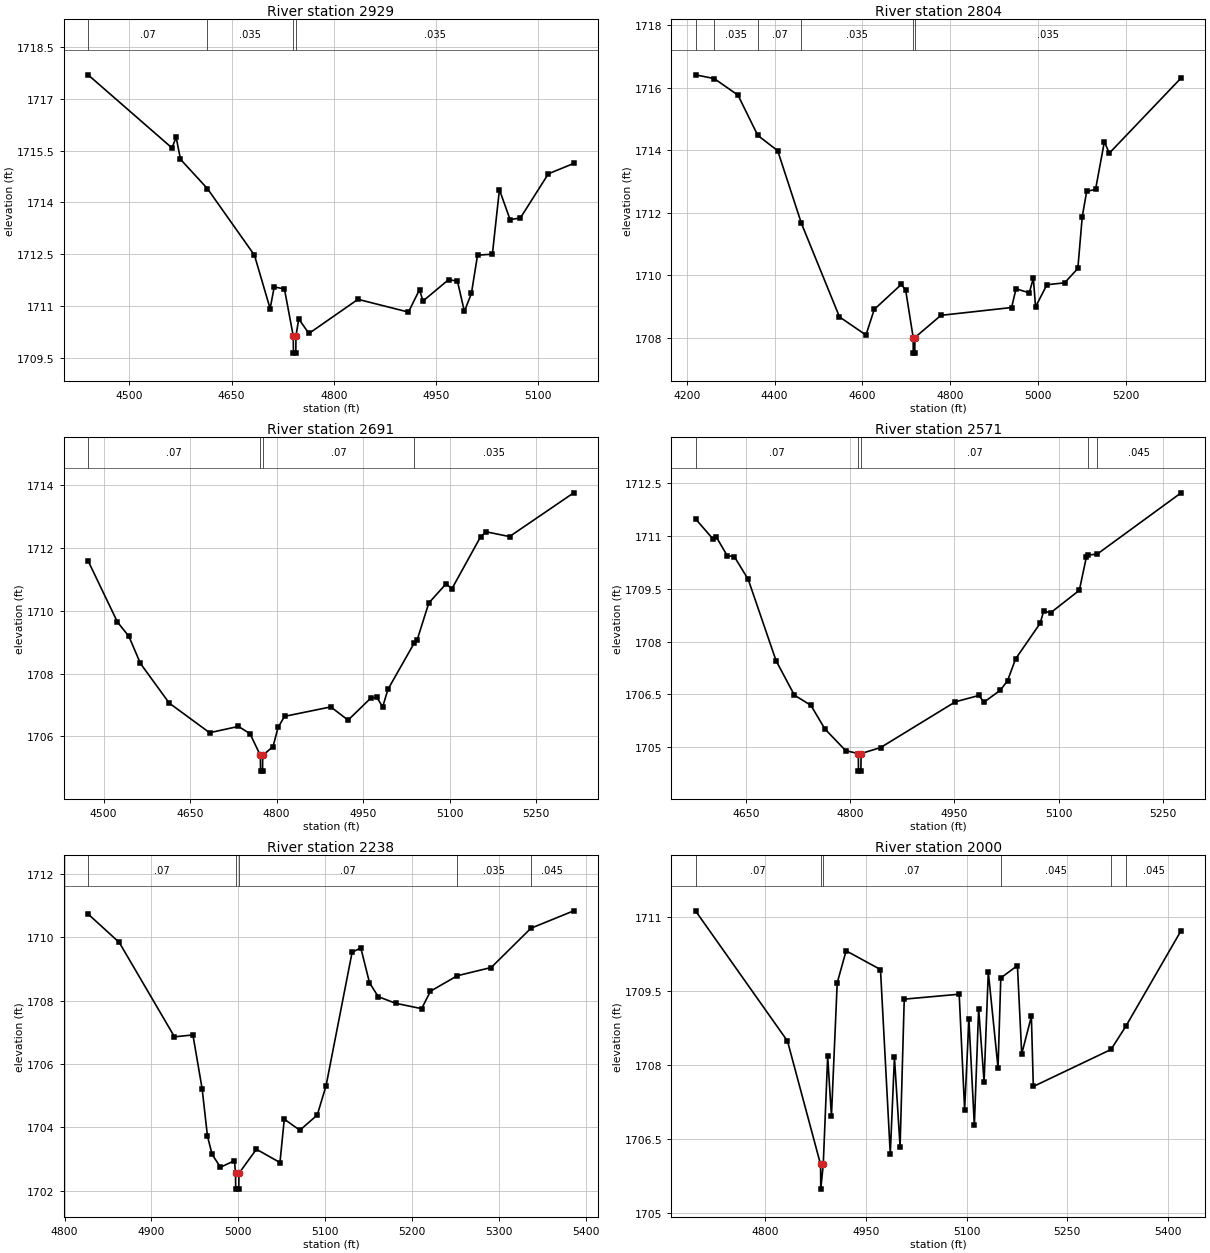
Type RM Length L Ch R = 1,2929,125,125,125
BEGIN DESCRIPTION:
Elm 01 54 5.0
END DESCRIPTION:
XS GIS Cut Line= 3
      1570162.03      6863000.39      1569904.96      6862619.20
      1569658.81      6862561.90
#Sta/Elev= 30
  4439.5 1717.70  4562.6 1715.58  4568.7 1715.89  4575.1 1715.25  4614.6 1714.40
  4683.6 1712.47  4706.6 1710.92  4712.6 1711.55  4727.6 1711.49  4740.5 1710.13
  4740.8 1709.63  4744.3 1709.63  4744.5 1710.13  4748.6 1710.62  4763.5 1710.20
  4835.5 1711.19  4909.5 1710.82  4925.8 1711.47  4930.9 1711.14  4968.4 1711.76
  4981.4 1711.72  4991.6 1710.84  5001.9 1711.36  5010.9 1712.47  5032.7 1712.50
  5043.0 1714.37  5058.7 1713.50  5073.8 1713.55  5114.8 1714.83  5152.0 1715.13
#Mann=4,-1,0
  4439.5    0.07       0  4614.6   0.035       0  4740.5   0.035       0
  4744.5   0.035       0
Bank Sta=4740.5,4744.5
Exp/Cntr=0.3,0.1

Type RM Length L Ch R = 1,2804,113,113,113
BEGIN DESCRIPTION:
Elm 01 54 2890.57
END DESCRIPTION:
XS GIS Cut Line= 3
      1570681.23      6862618.31      1569865.68      6862527.92
      1569581.44      6862564.32
#Sta/Elev= 30
  4219.6 1716.41  4262.3 1716.29  4316.4 1715.76  4361.6 1714.47  4407.0 1713.98
  4460.9 1711.66  4547.8 1708.66  4608.2 1708.08  4627.1 1708.90  4688.7 1709.70
  4698.7 1709.52  4715.8 1708.00  4716.0 1707.50  4719.5 1707.50  4719.8 1708.00
  4779.2 1708.71  4940.2 1708.96  4950.3 1709.56  4980.5 1709.43  4989.8 1709.90
  4994.8 1708.98  5020.7 1709.69  5061.0 1709.75  5091.2 1710.21  5101.3 1711.87
  5111.4 1712.68  5131.6 1712.74  5151.7 1714.27  5162.9 1713.90  5326.7 1716.31
#Mann=6,-1,0
  4219.6    0.07       0  4262.3   0.035       0  4361.6    0.07       0
  4460.9   0.035       0  4715.8   0.035       0  4719.8   0.035       0
Bank Sta=4715.8,4719.8
Exp/Cntr=0.3,0.1

Type RM Length L Ch R = 1,2691,120,120,120
BEGIN DESCRIPTION:
Elm 01 54 2690.88
END DESCRIPTION:
XS GIS Cut Line= 3
      1570515.78      6862446.38      1569991.51      6862456.80
      1569673.76      6862449.85
#Sta/Elev= 30
  4473.1 1711.58  4523.9 1709.64  4543.9 1709.18  4563.9 1708.32  4613.9 1707.06
  4683.9 1706.12  4733.9 1706.32  4753.9 1706.09  4771.9 1705.40  4772.2 1704.90
  4775.7 1704.90  4775.9 1705.40  4793.9 1705.68  4802.6 1706.29  4813.9 1706.64
  4894.0 1706.94  4924.0 1706.52  4964.0 1707.23  4974.0 1707.24  4984.0 1706.94
  4993.2 1707.50  5038.8 1708.97  5044.0 1709.08  5064.0 1710.24  5094.0 1710.85
  5104.0 1710.69  5154.0 1712.35  5164.0 1712.50  5204.0 1712.35  5315.3 1713.74
#Mann=4,-1,0
  4473.1    0.07       0  4771.9    0.07       0  4775.9    0.07       0
  5038.8   0.035       0
Bank Sta=4771.9,4775.9
Exp/Cntr=0.3,0.1

Type RM Length L Ch R = 1,2571,333,333,333
BEGIN DESCRIPTION:
Elm 01 54 2570.82
END DESCRIPTION:
XS GIS Cut Line= 3
      1570510.58      6862380.41      1570135.61      6862413.40
      1569823.11      6862331.80
#Sta/Elev= 30
  4577.2 1711.49  4602.3 1710.92  4607.3 1710.97  4623.0 1710.44  4633.0 1710.42
  4653.1 1709.77  4693.2 1707.46  4719.6 1706.48  4743.4 1706.19  4763.5 1705.52
  4793.6 1704.90  4811.7 1704.82  4811.9 1704.32  4815.4 1704.32  4815.7 1704.82
  4843.8 1704.99  4951.4 1706.29  4985.3 1706.47  4992.6 1706.28  5016.3 1706.62
  5026.6 1706.89  5038.2 1707.51  5073.5 1708.52  5078.7 1708.87  5088.6 1708.82
  5130.0 1709.46  5140.3 1710.42  5142.6 1710.46  5155.8 1710.49  5276.6 1712.23
#Mann=5,-1,0
  4577.2    0.07       0  4811.7    0.07       0  4815.7    0.07       0
  5142.6   0.035       0  5155.8   0.045       0
Bank Sta=4811.7,4815.7
Exp/Cntr=0.3,0.1

Type RM Length L Ch R = 1,2238,238,238,238
BEGIN DESCRIPTION:
Elm 01 54 2237.89
END DESCRIPTION:
XS GIS Cut Line= 3
      1570468.91      6862328.31      1570304.01      6862271.04
      1569920.29      6862286.66
#Sta/Elev= 30
  4827.1 1710.74  4863.0 1709.84  4926.5 1706.86  4947.7 1706.92  4958.3 1705.22
  4964.4 1703.73  4969.7 1703.15  4979.4 1702.74  4995.5 1702.95  4996.7 1702.55
  4996.9 1702.05  5000.4 1702.05  5000.7 1702.55  5020.7 1703.31  5047.8 1702.89
  5052.8 1704.26  5070.7 1703.91  5090.7 1704.39  5100.8 1705.31  5130.8 1709.53
  5140.8 1709.67  5150.8 1708.57  5160.8 1708.13  5180.8 1707.92  5210.8 1707.75
  5220.9 1708.30  5251.8 1708.79  5290.8 1709.05  5336.5 1710.29  5385.7 1710.84
#Mann=5,-1,0
  4827.1    0.07       0  4996.7    0.07       0  5000.7    0.07       0
  5251.8   0.035       0  5336.5   0.045       0
Bank Sta=4996.7,5000.7
Exp/Cntr=0.3,0.1

Type RM Length L Ch R = 1,2000,94,94,94
BEGIN DESCRIPTION:
Elm 01 54 1998.4
END DESCRIPTION:
XS GIS Cut Line= 6
      1570540.46      6862268.56      1570332.16      6862155.12
      1570262.34      6862102.63      1570200.91      6862103.06
      1570127.23      6862197.46      1569913.38      6862154.72
#Sta/Elev= 30
  4695.8 1711.12  4832.9 1708.48  4882.2 1705.98  4882.5 1705.48  4886.2 1705.98
  4892.8 1708.17  4898.4 1706.96  4907.0 1709.66  4920.3 1710.31  4971.5 1709.93
  4986.1 1706.19  4992.3 1708.15  5000.7 1706.34  5006.9 1709.33  5088.8 1709.43
  5096.9 1707.09  5103.3 1708.92  5111.4 1706.77  5117.8 1709.14  5125.9 1707.66
  5132.2 1709.88  5146.7 1707.94  5150.8 1709.76  5175.6 1710.01  5182.0 1708.22
  5196.4 1708.98  5199.3 1707.56  5315.1 1708.31  5337.6 1708.79  5419.6 1710.72
#Mann=6,-1,0
  4695.8    0.07       0  4882.2    0.07       0  4886.2    0.07       0
  5150.8   0.045       0  5315.1   0.035       0  5337.6   0.045       0
Bank Sta=4882.2,4886.2
Exp/Cntr=0.3,0.1