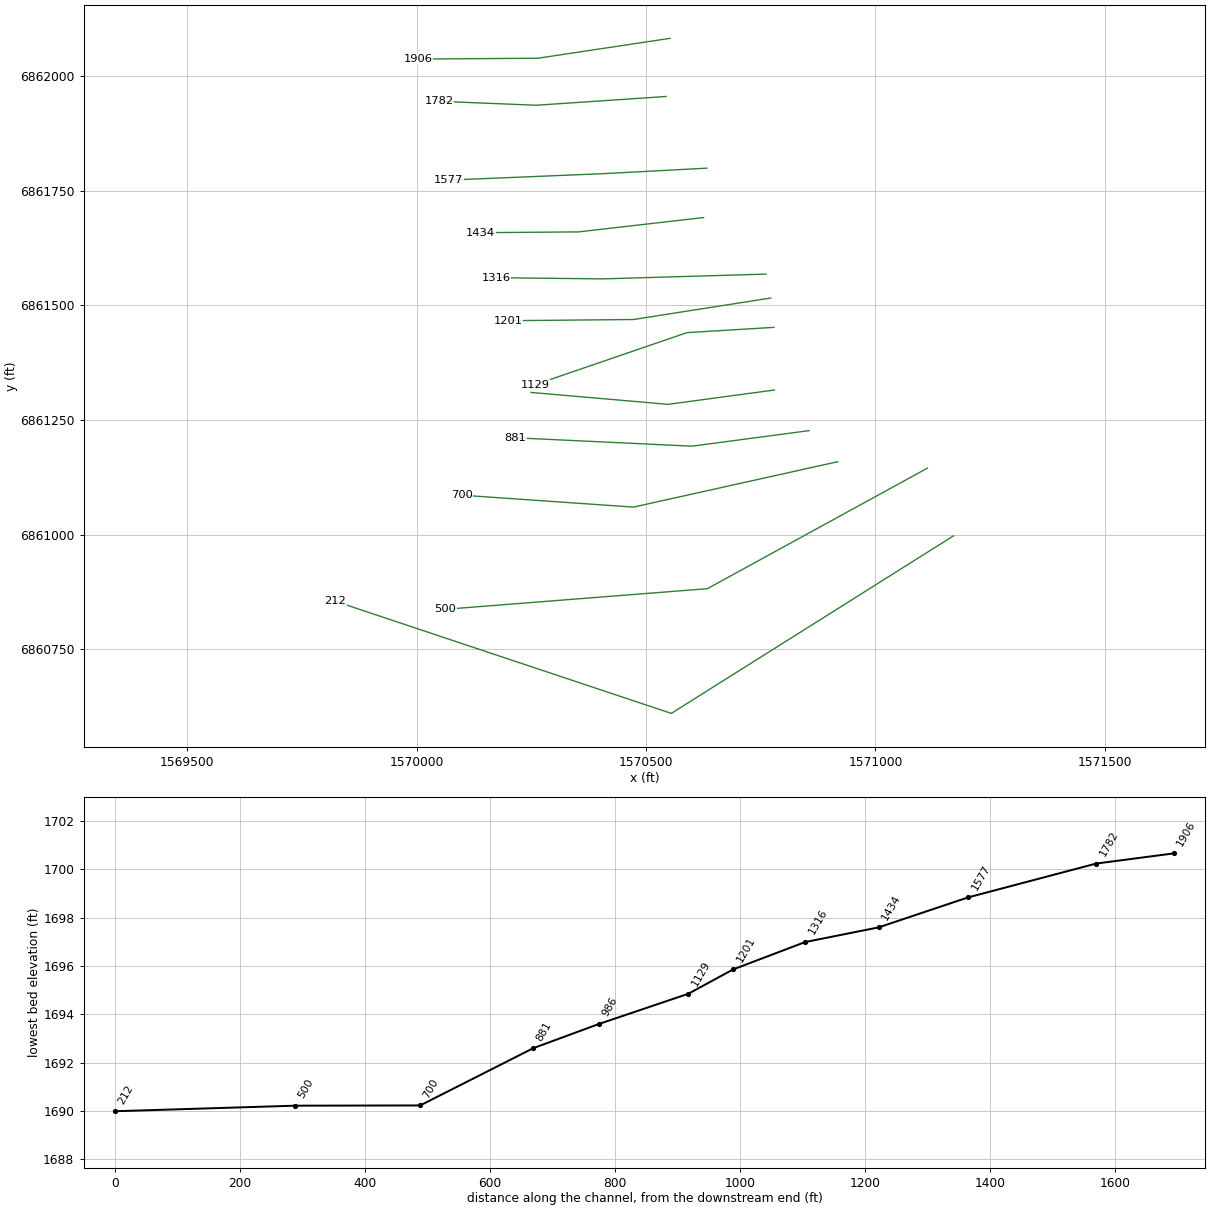
HEC-RAS study Elm 01 54.prj: Elm 01 54 Base Level Engineering

--- Elm 01 54.g01 (geometry) --- (continued)

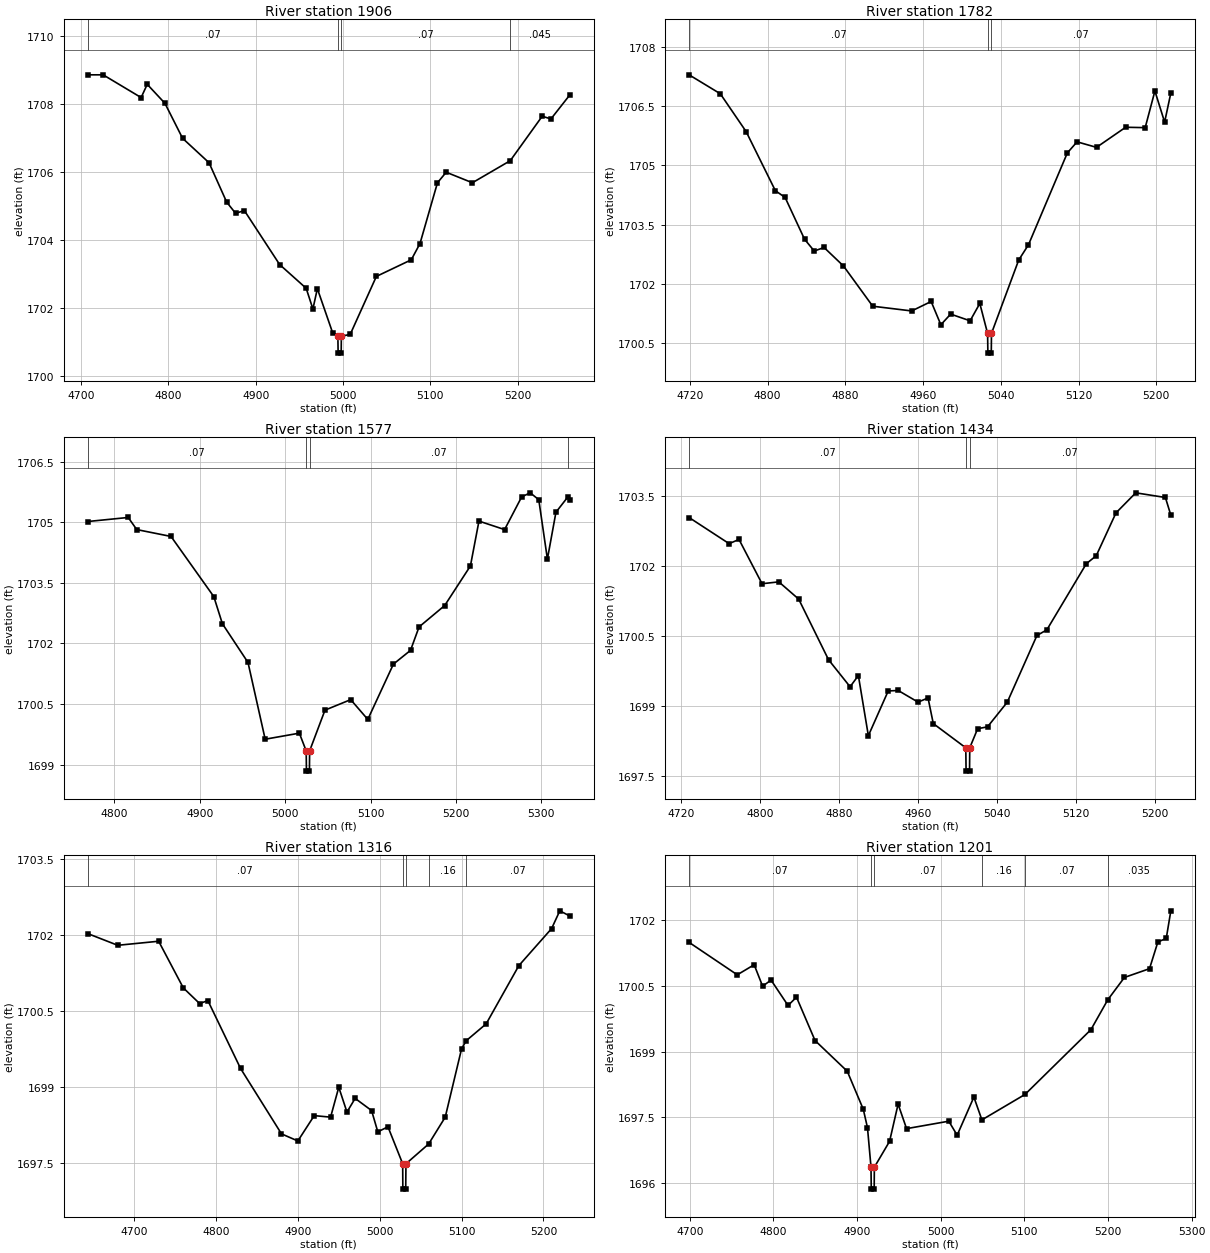
Type RM Length L Ch R = 1,1906,124,124,124
BEGIN DESCRIPTION:
Elm 01 54 1905.63
END DESCRIPTION:
XS GIS Cut Line= 3
      1570552.27      6862081.80      1570264.08      6862038.40
      1570003.62      6862036.66
#Sta/Elev= 30
  4707.7 1708.86  4725.2 1708.86  4768.7 1708.19  4775.7 1708.58  4796.0 1708.02
  4816.2 1706.99  4846.5 1706.27  4866.7 1705.11  4876.9 1704.78  4887.0 1704.86
  4927.4 1703.27  4957.8 1702.57  4965.5 1701.96  4970.6 1702.56  4988.1 1701.26
  4994.1 1701.16  4994.4 1700.66  4997.9 1700.66  4998.1 1701.16  5008.2 1701.21
  5038.2 1702.92  5078.2 1703.41  5088.2 1703.89  5108.2 1705.68  5118.2 1705.99
  5148.2 1705.68  5191.6 1706.33  5228.2 1707.64  5238.2 1707.56  5259.6 1708.26
#Mann=4,-1,0
  4707.7    0.07       0  4994.1    0.07       0  4998.1    0.07       0
  5191.6   0.045       0
Bank Sta=4994.1,4998.1
Exp/Cntr=0.3,0.1

Type RM Length L Ch R = 1,1782,205,205,205
BEGIN DESCRIPTION:
Elm 01 54 1781.5
END DESCRIPTION:
XS GIS Cut Line= 3
      1570543.56      6861955.06      1570260.61      6861935.97
      1570048.58      6861944.58
#Sta/Elev= 30
  4719.2 1707.30  4751.3 1706.82  4777.9 1705.86  4808.0 1704.36  4818.0 1704.19
  4838.0 1703.13  4848.0 1702.83  4858.1 1702.92  4878.1 1702.45  4908.2 1701.43
  4948.3 1701.31  4968.3 1701.55  4978.3 1700.96  4988.4 1701.23  5008.4 1701.06
  5018.4 1701.50  5026.4 1700.74  5026.7 1700.24  5030.2 1700.24  5030.4 1700.74
  5058.4 1702.60  5068.5 1702.99  5108.5 1705.32  5118.5 1705.60  5138.5 1705.46
  5168.5 1705.97  5188.6 1705.96  5198.6 1706.89  5208.6 1706.10  5215.0 1706.84
#Mann=3,-1,0
  4719.2    0.07       0  5026.4    0.07       0  5030.4    0.07       0
Bank Sta=5026.4,5030.4
Exp/Cntr=0.3,0.1

Type RM Length L Ch R = 1,1577,143,143,143
BEGIN DESCRIPTION:
Elm 01 54 1576.56
END DESCRIPTION:
XS GIS Cut Line= 3
      1570632.16      6861798.81      1570402.97      6861786.66
      1570068.97      6861772.82
#Sta/Elev= 30
  4769.2 1705.02  4816.4 1705.12  4826.4 1704.82  4866.5 1704.65  4916.6 1703.16
  4926.6 1702.49  4956.6 1701.53  4976.7 1699.63  5016.7 1699.78  5024.7 1699.34
  5025.0 1698.84  5028.5 1698.84  5028.7 1699.34  5046.7 1700.35  5076.8 1700.61
  5096.8 1700.12  5126.8 1701.49  5146.8 1701.83  5156.8 1702.41  5186.8 1702.94
  5216.9 1703.92  5226.9 1705.03  5256.9 1704.82  5276.9 1705.63  5286.9 1705.73
  5296.9 1705.56  5307.0 1704.09  5317.0 1705.25  5331.0 1705.63  5333.0 1705.56
#Mann=4,-1,0
  4769.2    0.07       0  5024.7    0.07       0  5028.7    0.07       0
  5331.0   0.045       0
Bank Sta=5024.7,5028.7
Exp/Cntr=0.3,0.1

Type RM Length L Ch R = 1,1434,118,118,118
BEGIN DESCRIPTION:
Elm 01 54 1433.74
END DESCRIPTION:
XS GIS Cut Line= 3
      1570625.22      6861691.18      1570352.62      6861659.92
      1570139.51      6861658.19
#Sta/Elev= 30
  4728.4 1703.04  4768.9 1702.48  4778.9 1702.57  4802.2 1701.62  4819.2 1701.66
  4839.3 1701.29  4869.5 1699.99  4891.3 1699.41  4899.7 1699.65  4909.8 1698.36
  4929.9 1699.32  4940.0 1699.33  4960.1 1699.08  4970.2 1699.17  4975.5 1698.62
  5008.4 1698.10  5008.7 1697.60  5012.2 1697.60  5012.4 1698.10  5020.4 1698.51
  5030.4 1698.55  5050.4 1699.08  5080.4 1700.51  5090.4 1700.63  5130.4 1702.05
  5140.4 1702.22  5160.4 1703.14  5180.4 1703.57  5210.4 1703.47  5215.9 1703.09
#Mann=3,-1,0
  4728.4    0.07       0  5008.4    0.07       0  5012.4    0.07       0
Bank Sta=5008.4,5012.4
Exp/Cntr=0.3,0.1

Type RM Length L Ch R = 1,1316,115,115,115
BEGIN DESCRIPTION:
Elm 01 54 1315.64
END DESCRIPTION:
XS GIS Cut Line= 3
      1570761.51      6861567.91      1570404.71      6861557.49
      1570172.98      6861560.10
#Sta/Elev= 30
  4643.3 1702.03  4679.8 1701.80  4729.8 1701.88  4759.9 1700.96  4779.9 1700.65
  4789.9 1700.71  4829.9 1699.37  4879.9 1698.08  4899.9 1697.94  4919.9 1698.44
  4939.9 1698.41  4949.9 1699.00  4959.9 1698.51  4969.9 1698.78  4990.0 1698.54
  4997.6 1698.12  5010.0 1698.22  5028.0 1697.49  5028.2 1696.99  5031.7 1696.99
  5032.0 1697.49  5059.7 1697.88  5080.0 1698.41  5100.0 1699.76  5105.8 1699.92
  5130.0 1700.25  5170.0 1701.40  5210.0 1702.13  5220.0 1702.48  5232.0 1702.38
#Mann=5,-1,0
  4643.3    0.07       0  5028.0    0.07       0  5032.0    0.07       0
  5059.7    0.16       0  5105.8    0.07       0
Bank Sta=5028,5032
Exp/Cntr=0.3,0.1

Type RM Length L Ch R = 1,1201,72,72,72
BEGIN DESCRIPTION:
Elm 01 54 1200.84
END DESCRIPTION:
XS GIS Cut Line= 3
      1570771.86      6861515.82      1570472.41      6861468.95
      1570199.52      6861466.35
#Sta/Elev= 30
  4699.1 1701.49  4756.7 1700.75  4776.9 1700.98  4787.0 1700.49  4797.1 1700.63
  4817.4 1700.05  4827.5 1700.24  4849.7 1699.25  4888.2 1698.55  4907.4 1697.68
  4912.4 1697.26  4916.6 1696.36  4916.9 1695.86  4920.4 1695.86  4920.6 1696.36
  4938.8 1696.95  4949.0 1697.80  4959.1 1697.24  5009.6 1697.41  5019.6 1697.09
  5039.6 1697.96  5049.2 1697.44  5100.7 1698.02  5179.6 1699.50  5199.7 1700.18
  5219.6 1700.69  5249.6 1700.89  5259.6 1701.50  5269.6 1701.58  5275.1 1702.21
#Mann=6,-1,0
  4699.1    0.07       0  4916.6    0.07       0  4920.6    0.07       0
  5049.2    0.16       0  5100.7    0.07       0  5199.7   0.035       0
Bank Sta=4916.6,4920.6
Exp/Cntr=0.3,0.1

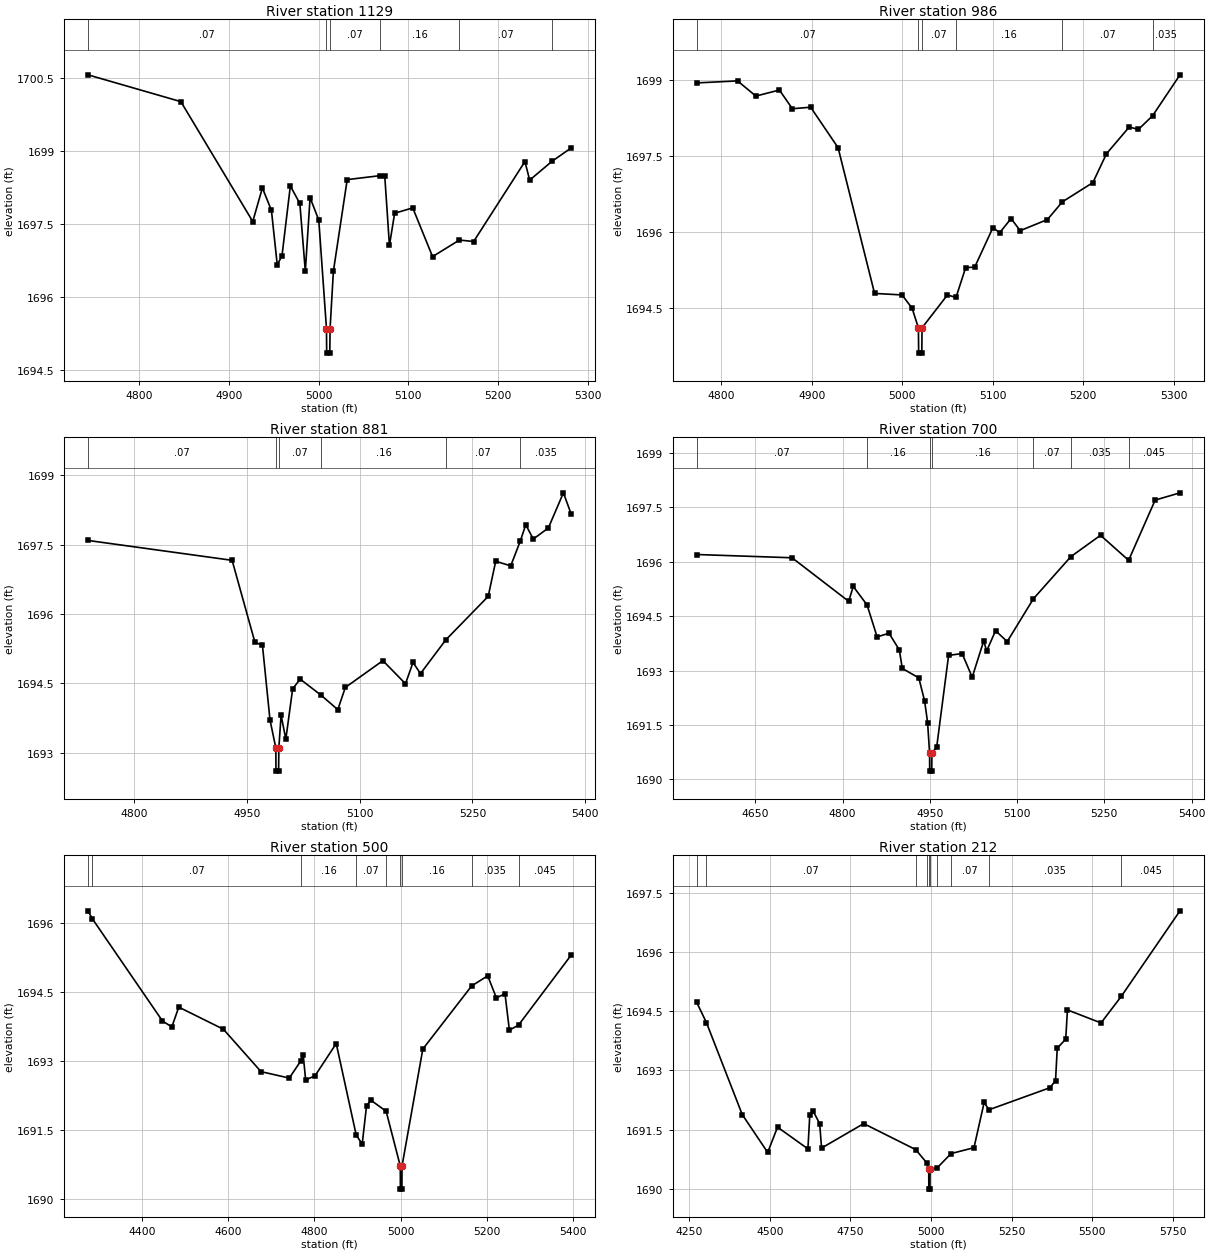
Type RM Length L Ch R = 1,1129,143,143,143
BEGIN DESCRIPTION:
Elm 01 54 1089.77
END DESCRIPTION:
XS GIS Cut Line= 3
      1570778.42      6861451.87      1570589.00      6861440.35
      1570258.73      6861327.14
#Sta/Elev= 30
  4742.8 1700.56  4846.4 1700.01  4926.6 1697.55  4937.3 1698.24  4947.4 1697.78
  4953.9 1696.66  4959.2 1696.85  4968.5 1698.28  4979.1 1697.92  4985.2 1696.53
  4990.5 1698.04  5000.2 1697.58  5008.8 1695.35  5009.0 1694.85  5012.5 1694.85
  5012.8 1695.35  5016.5 1696.53  5031.9 1698.41  5068.0 1698.49  5073.8 1698.48
  5079.0 1697.06  5084.8 1697.72  5105.0 1697.83  5127.1 1696.83  5157.0 1697.17
  5172.9 1697.14  5230.1 1698.78  5235.4 1698.40  5260.6 1698.79  5281.7 1699.06
#Mann=6,-1,0
  4742.8    0.07       0  5008.8    0.07       0  5012.8    0.07       0
  5068.0    0.16       0  5157.0    0.07       0  5260.6   0.035       0
Bank Sta=5008.8,5012.8
Exp/Cntr=0.3,0.1

Type RM Length L Ch R = 1,986,105,105,105
BEGIN DESCRIPTION:
Elm 01 54 985.84
END DESCRIPTION:
XS GIS Cut Line= 3
      1570779.66      6861315.30      1570547.93      6861284.06
      1570249.19      6861310.03
#Sta/Elev= 30
  4773.1 1698.94  4818.2 1698.98  4838.4 1698.68  4864.4 1698.80  4878.7 1698.43
  4898.9 1698.46  4929.2 1697.66  4969.5 1694.78  4999.8 1694.75  5010.9 1694.49
  5017.9 1694.10  5018.2 1693.60  5021.7 1693.60  5021.9 1694.10  5050.0 1694.75
  5059.4 1694.70  5070.1 1695.29  5080.1 1695.30  5100.2 1696.08  5107.7 1695.98
  5120.3 1696.26  5130.3 1696.02  5160.4 1696.24  5176.9 1696.59  5210.6 1696.97
  5225.6 1697.54  5250.8 1698.07  5260.8 1698.02  5276.5 1698.29  5306.8 1699.10
#Mann=6,-1,0
  4773.1    0.07       0  5017.9    0.07       0  5021.9    0.07       0
  5059.4    0.16       0  5176.9    0.07       0  5276.5   0.035       0
Bank Sta=5017.9,5021.9
Exp/Cntr=0.3,0.1

Type RM Length L Ch R = 1,881,181,181,181
BEGIN DESCRIPTION:
Elm 01 54 880.61
END DESCRIPTION:
XS GIS Cut Line= 3
      1570855.24      6861226.77      1570600.02      6861192.91
      1570214.60      6861211.14
#Sta/Elev= 30
  4738.1 1697.59  4930.0 1697.16  4960.3 1695.39  4970.4 1695.32  4980.4 1693.71
  4988.2 1693.10  4988.4 1692.60  4991.9 1692.60  4992.2 1693.10  4995.2 1693.81
  5001.5 1693.29  5010.6 1694.38  5020.6 1694.59  5048.6 1694.24  5070.7 1693.93
  5080.7 1694.41  5130.7 1694.99  5160.8 1694.49  5170.8 1694.95  5180.8 1694.71
  5214.5 1695.44  5270.9 1696.38  5280.9 1697.14  5300.9 1697.04  5313.7 1697.58
  5320.9 1697.93  5330.9 1697.62  5351.0 1697.86  5371.0 1698.62  5381.4 1698.16
#Mann=6,-1,0
  4738.1    0.07       0  4988.2    0.07       0  4992.2    0.07       0
  5048.6    0.16       0  5214.5    0.07       0  5313.7   0.035       0
Bank Sta=4988.2,4992.2
Exp/Cntr=0.3,0.1

Type RM Length L Ch R = 1,700,200,200,200
BEGIN DESCRIPTION:
Elm 01 54 699.86
END DESCRIPTION:
XS GIS Cut Line= 3
      1570917.72      6861159.05      1570472.41      6861060.10
      1570098.68      6861086.05
#Sta/Elev= 30
  4549.2 1696.20  4713.1 1696.11  4810.4 1694.91  4818.3 1695.32  4842.0 1694.81
  4859.3 1693.93  4879.8 1694.03  4897.5 1693.57  4902.6 1693.06  4931.0 1692.80
  4941.0 1692.16  4946.1 1691.57  4949.5 1690.73  4949.7 1690.23  4953.2 1690.23
  4953.5 1690.73  4961.7 1690.89  4982.2 1693.42  5005.4 1693.47  5022.8 1692.82
  5042.6 1693.82  5047.6 1693.54  5062.9 1694.10  5083.0 1693.80  5128.0 1694.98
  5192.3 1696.14  5243.4 1696.73  5291.7 1696.04  5337.3 1697.70  5380.0 1697.90
#Mann=7,-1,0
  4549.2    0.07       0  4842.0    0.16       0  4949.5    0.07       0
  4953.5    0.16       0  5128.0    0.07       0  5192.3   0.035       0
  5291.7   0.045       0
Bank Sta=4949.5,4953.5
Exp/Cntr=0.3,0.1

Type RM Length L Ch R = 1,500,288,288,288
BEGIN DESCRIPTION:
Elm 01 54 480.285
END DESCRIPTION:
XS GIS Cut Line= 3
      1571113.12      6861144.97      1570633.51      6860882.28
      1570062.11      6860837.36
#Sta/Elev= 30
  4275.1 1696.26  4285.1 1696.09  4447.7 1693.87  4469.5 1693.74  4485.6 1694.17
  4589.0 1693.69  4676.2 1692.77  4741.7 1692.63  4768.3 1693.00  4773.9 1693.14
  4779.6 1692.59  4801.4 1692.68  4850.5 1693.38  4896.9 1691.39  4910.7 1691.20
  4920.8 1692.03  4930.8 1692.15  4966.2 1691.91  4999.0 1690.72  4999.2 1690.22
  5002.7 1690.22  5003.0 1690.72  5051.2 1693.26  5164.4 1694.63  5201.6 1694.85
  5221.7 1694.37  5241.7 1694.46  5251.8 1693.67  5273.0 1693.78  5395.1 1695.30
#Mann=9,-1,0
  4275.1    0.16       0  4285.1    0.07       0  4768.3    0.16       0
  4896.9    0.07       0  4966.2    0.16       0  4999.0    0.07       0
  5003.0    0.16       0  5164.4   0.035       0  5273.0   0.045       0
Bank Sta=4999,5003
Exp/Cntr=0.3,0.1

Type RM Length L Ch R = 1,212,0,0,0
BEGIN DESCRIPTION:
Elm 01 54 211.641
END DESCRIPTION:
XS GIS Cut Line= 3
      1571170.30      6860997.58      1570555.03      6860610.51
      1569822.68      6860854.75
#Sta/Elev= 30
  4273.1 1694.72  4303.1 1694.21  4414.2 1691.88  4493.1 1690.92  4523.7 1691.56
  4617.9 1691.01  4623.8 1691.87  4633.2 1691.98  4654.4 1691.65  4660.3 1691.03
  4791.0 1691.65  4952.5 1690.99  4988.0 1690.64  4992.7 1690.49  4993.0 1689.99
  4996.5 1689.99  4996.7 1690.49  5017.8 1690.52  5061.8 1690.89  5133.0 1691.04
  5164.7 1692.19  5179.3 1692.00  5369.0 1692.56  5386.0 1692.74  5391.3 1693.56
  5417.6 1693.79  5422.9 1694.53  5527.1 1694.20  5589.6 1694.87  5772.0 1697.04
#Mann=10,-1,0
  4273.1    0.16       0  4303.1    0.07       0  4952.5   0.035       0
  4988.0    0.07       0  4992.7    0.07       0  4996.7    0.07       0
  5017.8   0.035       0  5061.8    0.07       0  5179.3   0.035       0
  5589.6   0.045       0
Bank Sta=4992.7,4996.7
Exp/Cntr=0.3,0.1

Chan Stop Cuts=-1