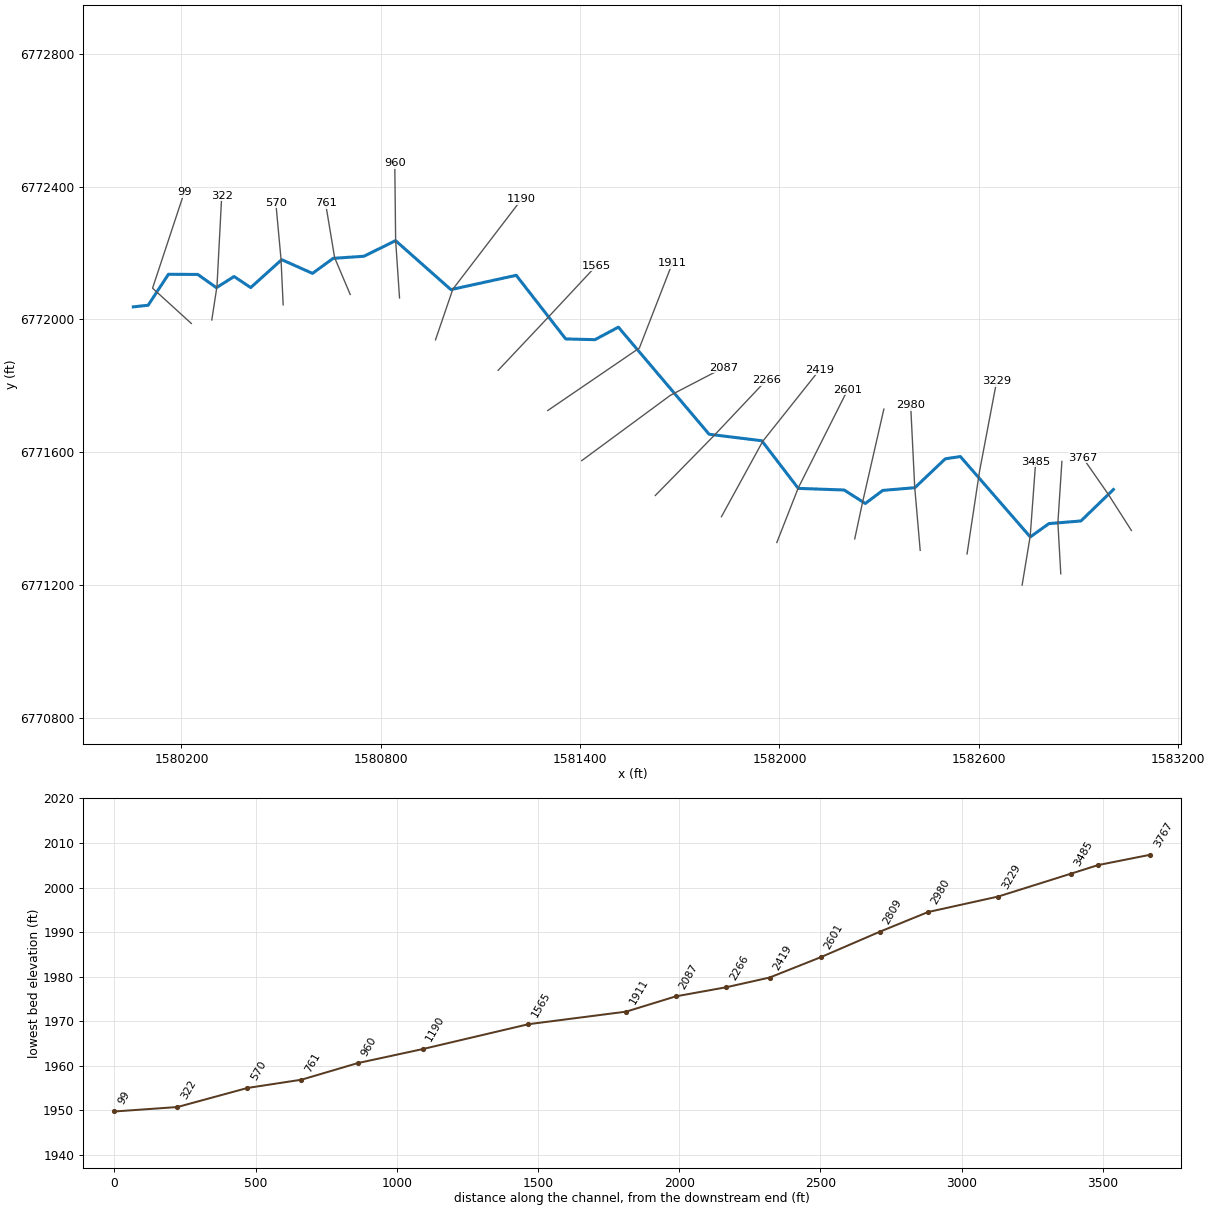
--- Elm 01 61.prj (project) ---

Proj Title=Elm 01 61 Base Level Engineering
Current Plan=p01
Default Exp/Contr=0.3,0.1
English Units
Geom File=g01
Flow File=f01
Plan File=p01
Y Axis Title=Elevation
X Axis Title(PF)=Main Channel Distance
X Axis Title(XS)=Station
BEGIN DESCRIPTION:
Elm 01 61
END DESCRIPTION:
DSS Export Rating Curves= 0
DSS Export Rating Curve Sorted= 0
DSS Export Volume Flow Curves= 0
DXF OffsetX= 0
DXF OffsetY= 0
DXF ScaleX= 1
DXF ScaleY= 10

--- Elm 01 61.p01 (plan) ---

Plan Title=Multiple Run
Short Identifier=Multiple
Geom File=g01
Flow File=f01
Subcritical Flow
K Sum by GR= 0
Std Step Tol= 0.01
Critical Tol= 0.01
Num of Std Step Trials= 20
Max Error Tol= 0.3
Flow Tol Ratio= 0.001
Split Flow NTrial= 30
Split Flow Tol= 0.02
Split Flow Ratio= 0.02
Log Output Level= 0
Friction Slope Method= 1
Unsteady Friction Slope Method= 2
Unsteady Bridges Friction Slope Method= 1
Parabolic Critical Depth
Global Vel Dist=  1 , 1 , 1
Global Log Level= 0
CheckData=True
Encroach Param= -1, 0, 0, 0
BEGIN DESCRIPTION:
Multiple Run
END DESCRIPTION:

--- Elm 01 61.f01 (steady flow) ---

Flow Title=Multiple
Number of Profiles=7
Profile Names=10-year,25-year,50-year,1pct_min,100-year,1pct_plu,500-year
River Rch & RM= Elm 01 61,Reach-1,3767
     110     146     175     131     210     289     305
Boundary for River Rch & Prof#=Elm 01 61,Reach-1,1
Up Type=0
Dn Type=3
Dn Slope=0.001
Boundary for River Rch & Prof#=Elm 01 61,Reach-1,2
Up Type=0
Dn Type=3
Dn Slope=0.001
Boundary for River Rch & Prof#=Elm 01 61,Reach-1,3
Up Type=0
Dn Type=3
Dn Slope=0.001
Boundary for River Rch & Prof#=Elm 01 61,Reach-1,4
Up Type=0
Dn Type=3
Dn Slope=0.001
Boundary for River Rch & Prof#=Elm 01 61,Reach-1,5
Up Type=0
Dn Type=3
Dn Slope=0.001
Boundary for River Rch & Prof#=Elm 01 61,Reach-1,6
Up Type=0
Dn Type=3
Dn Slope=0.001
Boundary for River Rch & Prof#=Elm 01 61,Reach-1,7
Up Type=0
Dn Type=3
Dn Slope=0.001

--- Elm 01 61.g01 (geometry) ---

Geom Title=Existing Conditions
Program Version=4.10

River Reach=Elm 01 61       ,Reach-1
Reach XY= 30
        1583005.        6771488.      1582907.45      6771393.46
      1582810.89      6771385.44      1582754.89      6771345.31
      1582544.37      6771587.45      1582498.96      6771580.52
      1582407.42      6771493.54       1582310.9      6771485.44
       1582258.3      6771446.08      1582194.56       6771486.6
      1582056.46      6771491.54      1581946.69      6771634.92
      1581788.24      6771654.43      1581515.06       6771976.9
      1581444.52      6771939.27      1581356.49      6771941.46
      1581207.55      6772133.01      1581010.89      6772089.96
      1580844.38       6772237.4      1580749.03      6772190.38
      1580656.58      6772184.11      1580594.29      6772138.82
      1580501.59      6772180.15      1580408.33      6772096.01
      1580358.34      6772129.43       1580305.1      6772095.79
      1580249.11      6772135.65      1580160.72      6772136.11
      1580099.65      6772042.97        1580055.        6772038.

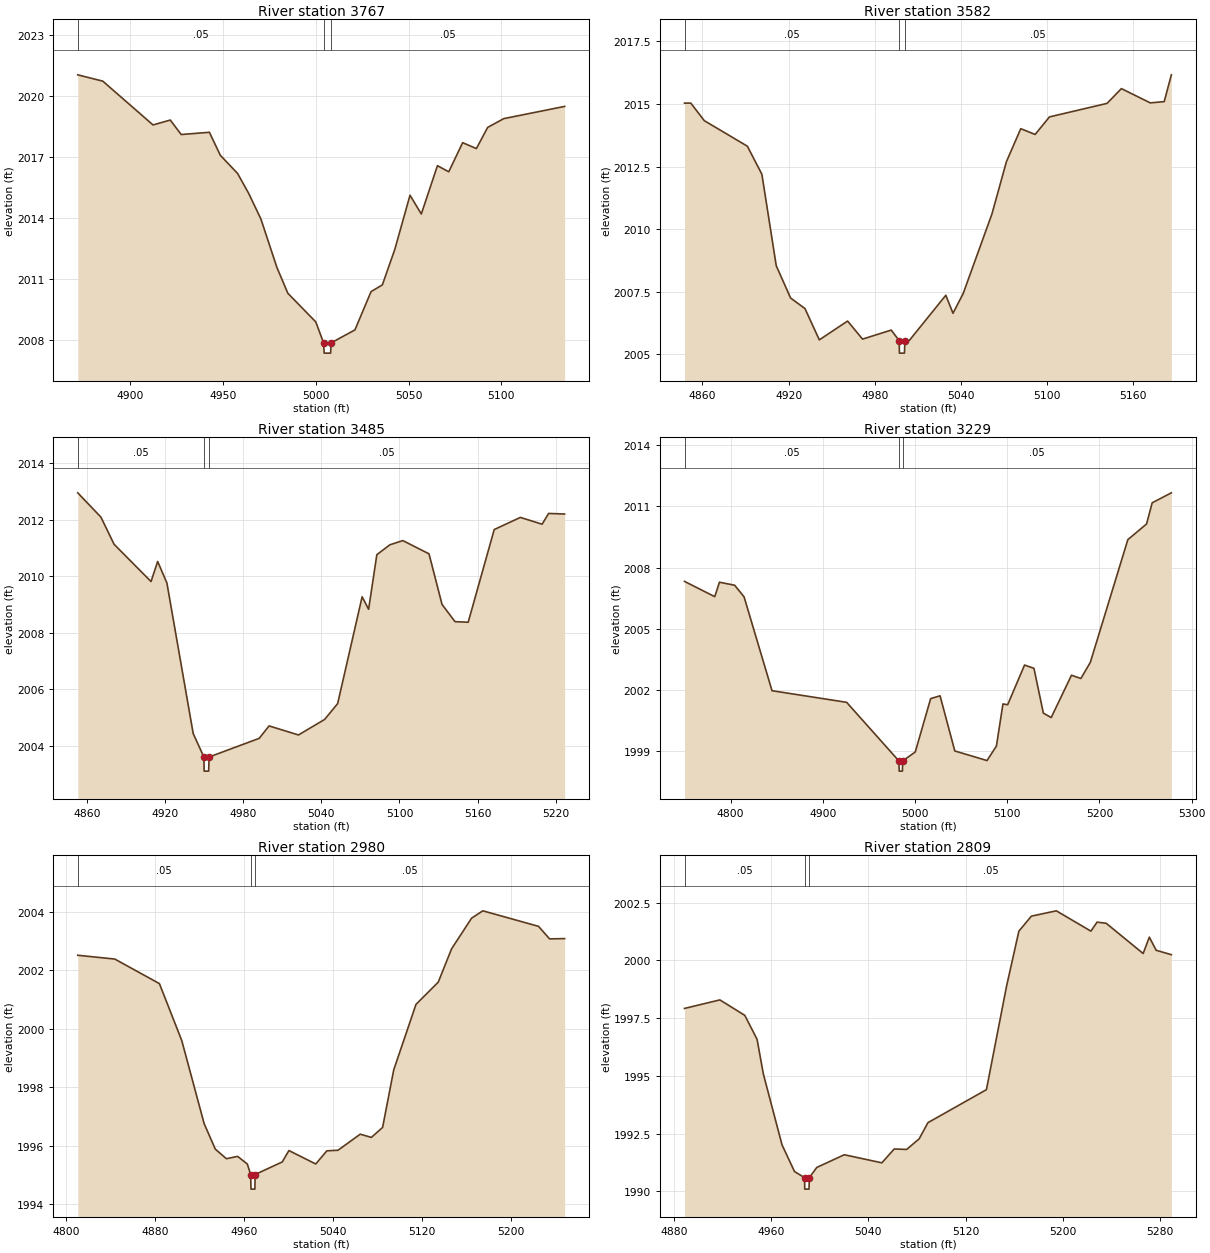
Type RM Length L Ch R = 1 ,3767    ,185,185,185
BEGIN DESCRIPTION:
Elm 01 61 3363.123
END DESCRIPTION:
XS GIS Cut Line= 3
      1583059.25      6771364.76      1582990.11      6771472.96
      1582913.62      6771583.22
#Sta/Elev= 30
  4871.6 2021.03  4885.1 2020.72  4912.2 2018.57  4921.5 2018.81  4927.4  2018.1
  4942.6 2018.21  4948.5 2017.08  4957.8 2016.19  4963.8 2015.21  4970.4 2013.95
    4979 2011.58  4984.9 2010.31    5000  2008.9  5004.2 2007.87  5004.5 2007.37
    5008 2007.37  5008.2 2007.87  5021.1 2008.51  5029.8 2010.39  5035.9 2010.72
  5042.6 2012.46  5050.8 2015.12  5056.9  2014.2  5065.6 2016.57  5071.7 2016.27
  5079.2  2017.7  5086.6 2017.41  5092.7 2018.45  5101.4 2018.88  5134.2 2019.48
#Mann= 3 ,-1 , 0
  4871.6     .05       0  5004.2     .05       0  5008.2     .05       0
Bank Sta=5004.2,5008.2
XS Rating Curve= 0 ,0
Exp/Cntr=0.3,0.1

Type RM Length L Ch R = 1 ,3582    ,97,97,97
BEGIN DESCRIPTION:
Elm 01 61 3582.28
END DESCRIPTION:
XS GIS Cut Line= 3
      1582846.67      6771234.24      1582837.99      6771387.93
      1582850.02       6771572.7
#Sta/Elev= 30
  4847.5 2015.03  4851.9 2015.03  4861.3 2014.33  4891.3 2013.31  4901.4 2012.19
  4911.4 2008.54  4921.4 2007.25  4931.4 2006.83  4941.4 2005.58  4961.1 2006.33
  4971.5 2005.61  4991.5 2005.97    4997 2005.55  4997.2 2005.05  5000.7 2005.05
    5001 2005.55    5004 2005.55  5029.5 2007.36  5034.5 2006.64  5041.6 2007.43
  5061.6  2010.6  5071.7 2012.69  5081.7 2014.01  5091.7 2013.78  5101.7 2014.48
  5141.8 2015.02  5151.8 2015.61  5171.9 2015.04  5181.6 2015.09  5186.6 2016.16
#Mann= 3 ,-1 , 0
  4847.5     .05       0    4997     .05       0    5001     .05       0
Bank Sta=4997,5001
XS Rating Curve= 0 ,0
Exp/Cntr=0.3,0.1

Type RM Length L Ch R = 1 ,3485    ,256,256,256
BEGIN DESCRIPTION:
Elm 01 61 3484.79
END DESCRIPTION:
XS GIS Cut Line= 3
      1582730.35      6771200.43      1582754.66        6771348.
      1582771.15      6771571.94
#Sta/Elev= 30
  4852.8 2012.95  4870.6 2012.09  4880.7 2011.13  4909.1 2009.81  4914.2 2010.52
  4921.3 2009.76  4941.5 2004.43  4949.7  2003.6  4949.9  2003.1  4953.4  2003.1
  4953.7  2003.6  4992.2 2004.26  4999.8  2004.7  5022.4 2004.38  5042.5 2004.93
  5052.5 2005.49  5071.3 2009.27  5076.3 2008.83  5082.6 2010.76  5092.6 2011.11
  5102.6 2011.26  5122.7 2010.79  5132.7    2009  5142.7 2008.39  5152.8 2008.37
  5172.8 2011.65  5192.9 2012.08  5209.6 2011.84  5214.6 2012.22  5226.9  2012.2
#Mann= 3 ,-1 , 0
  4852.8     .05       0  4949.7     .07       0  4953.7     .05       0
Bank Sta=4949.7,4953.7
XS Rating Curve= 0 ,0
Exp/Cntr=0.3,0.1

Type RM Length L Ch R = 1 ,3229    ,249,249,249
BEGIN DESCRIPTION:
Elm 01 61 3228.54
END DESCRIPTION:
XS GIS Cut Line= 3
      1582564.55      6771294.17      1582601.88      6771541.58
      1582653.68       6771814.4
#Sta/Elev= 30
  4750.1 2007.32  4782.9 2006.57    4788 2007.28  4804.5 2007.13  4814.7 2006.56
    4845 2001.95  4925.9 2001.38  4982.6  1998.5  4982.9    1998  4986.4    1998
  4986.6  1998.5  5000.3 1998.94    5017 2001.56  5027.2  2001.7  5043.2 1998.99
  5078.1 1998.52  5088.3 1999.23  5095.4  2001.3  5100.5 2001.26  5118.8 2003.21
    5129 2003.05  5139.2 2000.85  5147.7 2000.63  5169.7 2002.71  5179.9 2002.55
  5190.1 2003.34  5230.8 2009.37  5251.1 2010.14  5257.2 2011.18    5278 2011.67
#Mann= 3 ,-1 , 0
  4750.1     .05       0  4982.6     .05       0  4986.6     .05       0
Bank Sta=4982.6,4986.6
XS Rating Curve= 0 ,0
Exp/Cntr=0.3,0.1

Type RM Length L Ch R = 1 ,2980    ,171,171,171
BEGIN DESCRIPTION:
Elm 01 61 2980.37
END DESCRIPTION:
XS GIS Cut Line= 3
      1582423.49      6771304.86        1582407.      6771494.96
      1582394.85      6771741.45
#Sta/Elev= 30
  4810.7 2002.51    4844 2002.38  4884.1 2001.54  4904.2 1999.59  4924.3 1996.75
  4934.3 1995.88  4944.3 1995.55  4954.4 1995.63  4963.1 1995.37  4966.1 1995.01
  4966.4 1994.51  4969.9 1994.51  4970.1 1995.01  4994.5 1995.44  5000.5 1995.83
  5024.6 1995.37  5034.6 1995.82  5044.6 1995.84  5064.6 1996.39  5074.6 1996.28
  5084.7 1996.62  5094.7 1998.59  5114.7 2000.83  5134.7 2001.59  5146.7 2002.73
  5164.7 2003.78  5174.8 2004.03  5224.8  2003.5  5234.8 2003.07  5248.3 2003.08
#Mann= 3 ,-1 , 0
  4810.7     .05       0  4966.1     .05       0  4970.1     .05       0
Bank Sta=4966.1,4970.1
XS Rating Curve= 0 ,0
Exp/Cntr=0.3,0.1

Type RM Length L Ch R = 1 ,2809    ,208,208,208
BEGIN DESCRIPTION:
Elm 01 61 2808.56
END DESCRIPTION:
XS GIS Cut Line= 3
      1582226.44      6771339.55      1582249.88      6771448.95
      1582314.12      6771730.22
#Sta/Elev= 30
  4888.8 1997.92  4917.9 1998.29  4938.4 1997.62  4948.5 1996.58  4953.6 1995.09
    4969 1992.01  4979.3 1990.85  4987.5 1990.59  4987.7 1990.09  4991.2 1990.09
  4991.5 1990.59  4997.6 1991.03  5020.2 1991.58  5051.1 1991.23  5061.3 1991.83
  5071.5 1991.81  5081.8 1992.27    5089 1992.97  5137.1  1994.4  5153.6 1998.87
  5163.8 2001.27  5174.1 2001.92  5194.6 2002.15    5223 2001.27  5228.1 2001.66
  5235.6 2001.61    5266  2000.3  5271.1 2001.01  5276.7 2000.44  5289.2 2000.25
#Mann= 3 ,-1 , 0
  4888.8     .05       0  4987.5     .04       0  4991.5     .05       0
Bank Sta=4987.5,4991.5
XS Rating Curve= 0 ,0
Exp/Cntr=0.3,0.1

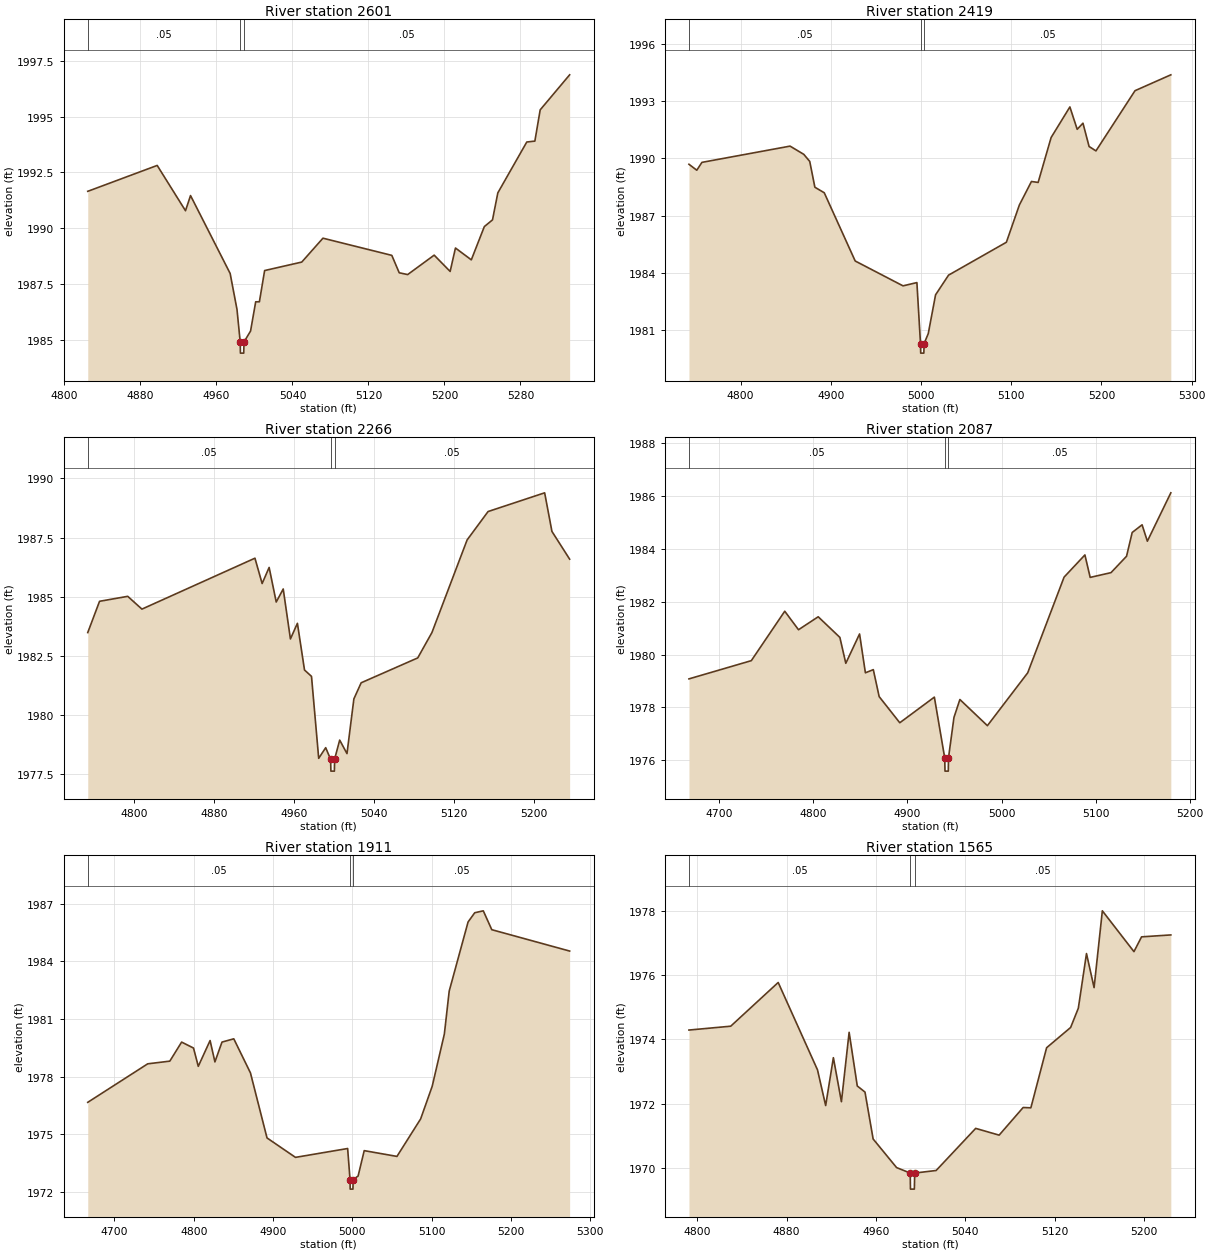
Type RM Length L Ch R = 1 ,2601    ,182,182,182
BEGIN DESCRIPTION:
Elm 01 61 2601.45
END DESCRIPTION:
XS GIS Cut Line= 3
      1581991.94      6771328.47      1582056.53      6771493.09
      1582205.15      6771788.25
#Sta/Elev= 30
  4824.5 1991.65  4897.6 1992.81  4927.4 1990.78  4932.7 1991.46  4974.4 1987.97
  4981.6 1986.36    4985  1984.9  4985.2  1984.4  4988.7  1984.4    4989  1984.9
  4995.9 1985.39  5001.3  1986.7  5005.2  1986.7  5010.7  1988.1  5049.8 1988.48
  5072.1 1989.55  5144.6 1988.78  5152.4    1988  5161.3 1987.92  5189.2 1988.79
    5206 1988.06  5211.6 1989.11  5228.3 1988.58    5242 1990.07  5250.6 1990.37
  5256.2 1991.58  5286.7 1993.86  5295.2  1993.9  5300.8  1995.3  5331.8 1996.87
#Mann= 3 ,-1 , 0
  4824.5     .05       0    4985     .05       0    4989     .05       0
Bank Sta=4985,4989
XS Rating Curve= 0 ,0
Exp/Cntr=0.3,0.1

Type RM Length L Ch R = 1 ,2419    ,153,153,153
BEGIN DESCRIPTION:
Elm 01 61 2418.98
END DESCRIPTION:
XS GIS Cut Line= 3
      1581825.29       6771406.3      1581949.59      6771633.36
      1582120.92      6771848.91
#Sta/Elev= 30
  4742.7 1989.69  4751.4 1989.38  4757.1 1989.79  4854.8 1990.64    4870 1990.21
  4876.6 1989.84  4882.3 1988.49  4892.7  1988.2    4927 1984.63    4980 1983.33
  4995.4  1983.5  4999.4 1980.31  4999.6 1979.81  5003.1 1979.81  5003.4 1980.31
    5008 1980.83  5016.1 1982.86  5030.5 1983.89  5094.6 1985.61    5109 1987.56
  5122.4 1988.79  5129.8 1988.74  5144.2 1991.09    5165 1992.69  5173.1 1991.52
  5179.5 1991.84  5186.3 1990.62  5193.9 1990.39  5237.2 1993.54  5276.9 1994.37
#Mann= 3 ,-1 , 0
  4742.7     .05       0  4999.4     .04       0  5003.4     .05       0
Bank Sta=4999.4,5003.4
XS Rating Curve= 0 ,0
Exp/Cntr=0.3,0.1

Type RM Length L Ch R = 1 ,2266    ,179,179,179
BEGIN DESCRIPTION:
Elm 01 61 2265.58
END DESCRIPTION:
XS GIS Cut Line= 3
      1581626.18      6771470.11      1581799.76      6771647.17
      1581960.58       6771817.5
#Sta/Elev= 30
  4753.3 1983.49  4765.1 1984.81  4793.3 1985.02  4807.5 1984.48  4920.6 1986.63
  4927.8 1985.56  4934.8 1986.24  4941.9 1984.78  4948.9 1985.33  4956.1 1983.22
  4963.1 1983.88  4970.2 1981.91  4977.2 1981.64  4984.4 1978.18  4991.4 1978.63
  4996.3 1978.14  4996.6 1977.64  5000.1 1977.64  5000.3 1978.14  5005.4 1978.95
  5012.7 1978.38  5019.6 1980.69  5026.9 1981.37  5083.5 1982.42  5097.7 1983.49
  5132.9  1987.4  5153.9  1988.6  5210.5 1989.39  5217.8 1987.76  5235.5 1986.59
#Mann= 3 ,-1 , 0
  4753.3     .05       0  4996.3     .05       0  5000.3     .05       0
Bank Sta=4996.3,5000.3
XS Rating Curve= 0 ,0
Exp/Cntr=0.3,0.1

Type RM Length L Ch R = 1 ,2087    ,176,176,176
BEGIN DESCRIPTION:
Elm 01 61 2120.19
END DESCRIPTION:
XS GIS Cut Line= 3
      1581404.81      6771575.13        1581672.      6771772.03
      1581831.39       6771854.8
#Sta/Elev= 30
  4668.1 1979.08  4734.3 1979.77  4769.8 1981.64  4784.4 1980.94  4805.3 1981.43
  4828.3 1980.65  4834.6 1979.67  4849.2 1980.78  4855.4 1979.31  4863.8 1979.43
    4870 1978.41  4891.9 1977.42  4928.6 1978.39  4939.6 1976.09  4939.9 1975.59
  4943.4 1975.59  4943.6 1976.09  4949.4 1977.62  4955.7  1978.3  4984.9 1977.31
  5027.7 1979.31  5066.3 1982.93  5088.4 1983.77    5094 1982.92  5116.1  1983.1
  5132.6 1983.72  5138.6 1984.62  5149.1 1984.91  5154.7 1984.29  5179.6 1986.12
#Mann= 3 ,-1 , 0
  4668.1     .05       0  4939.6     .03       0  4943.6     .05       0
Bank Sta=4939.6,4943.6
XS Rating Curve= 0 ,0
Exp/Cntr=0.3,0.1

Type RM Length L Ch R = 1 ,1911    ,346,346,346
BEGIN DESCRIPTION:
Elm 01 61 1910.595
END DESCRIPTION:
XS GIS Cut Line= 3
      1581302.56      6771725.99      1581578.21      6771914.06
      1581677.51      6772169.54
#Sta/Elev= 30
  4666.3 1976.67  4741.9 1978.67  4769.8 1978.81  4784.7  1979.8  4799.7 1979.49
  4805.7 1978.54  4820.6 1979.88  4826.7 1978.77  4835.6  1979.8  4850.5 1979.97
  4871.5  1978.2  4892.4 1974.82  4928.3 1973.81  4994.1 1974.27  4997.1 1972.66
  4997.3 1972.16  5000.8 1972.16  5001.1 1972.66  5007.3 1972.84    5015 1974.16
  5056.3 1973.86  5086.2 1975.81  5100.8 1977.51  5116.1 1980.22  5122.2 1982.45
    5146 1986.04  5154.4 1986.52  5165.2 1986.62  5175.9 1985.64  5274.1 1984.53
#Mann= 3 ,-1 , 0
  4666.3     .05       0  4997.1     .05       0  5001.1     .05       0
Bank Sta=4997.1,5001.1
XS Rating Curve= 0 ,0
Exp/Cntr=0.3,0.1

Type RM Length L Ch R = 1 ,1565    ,375,375,375
BEGIN DESCRIPTION:
Elm 01 61 1564.79
END DESCRIPTION:
XS GIS Cut Line= 3
       1581153.2      6771846.97      1581296.44       6771998.9
      1581448.32      6772161.63
#Sta/Elev= 30
  4792.6 1974.29    4830 1974.41  4872.5 1975.77  4907.7 1973.05    4915 1971.94
  4921.9 1973.43  4929.1 1972.06    4936 1974.22  4943.3 1972.55  4950.2 1972.36
  4957.5  1970.9  4978.5 1970.01  4990.7 1969.84  4990.9 1969.34  4994.4 1969.34
  4994.7 1969.84  5013.9 1969.92  5049.3 1971.23  5070.3 1971.02  5091.8 1971.88
  5098.7 1971.87  5112.8 1973.74  5134.3 1974.37  5141.2 1974.97  5148.5 1976.67
  5155.3 1975.61  5162.7    1978    5191 1976.73  5197.8 1977.19    5224 1977.25
#Mann= 3 ,-1 , 0
  4792.6     .05       0  4990.7     .03       0  4994.7     .05       0
Bank Sta=4990.7,4994.7
XS Rating Curve= 0 ,0
Exp/Cntr=0.3,0.1

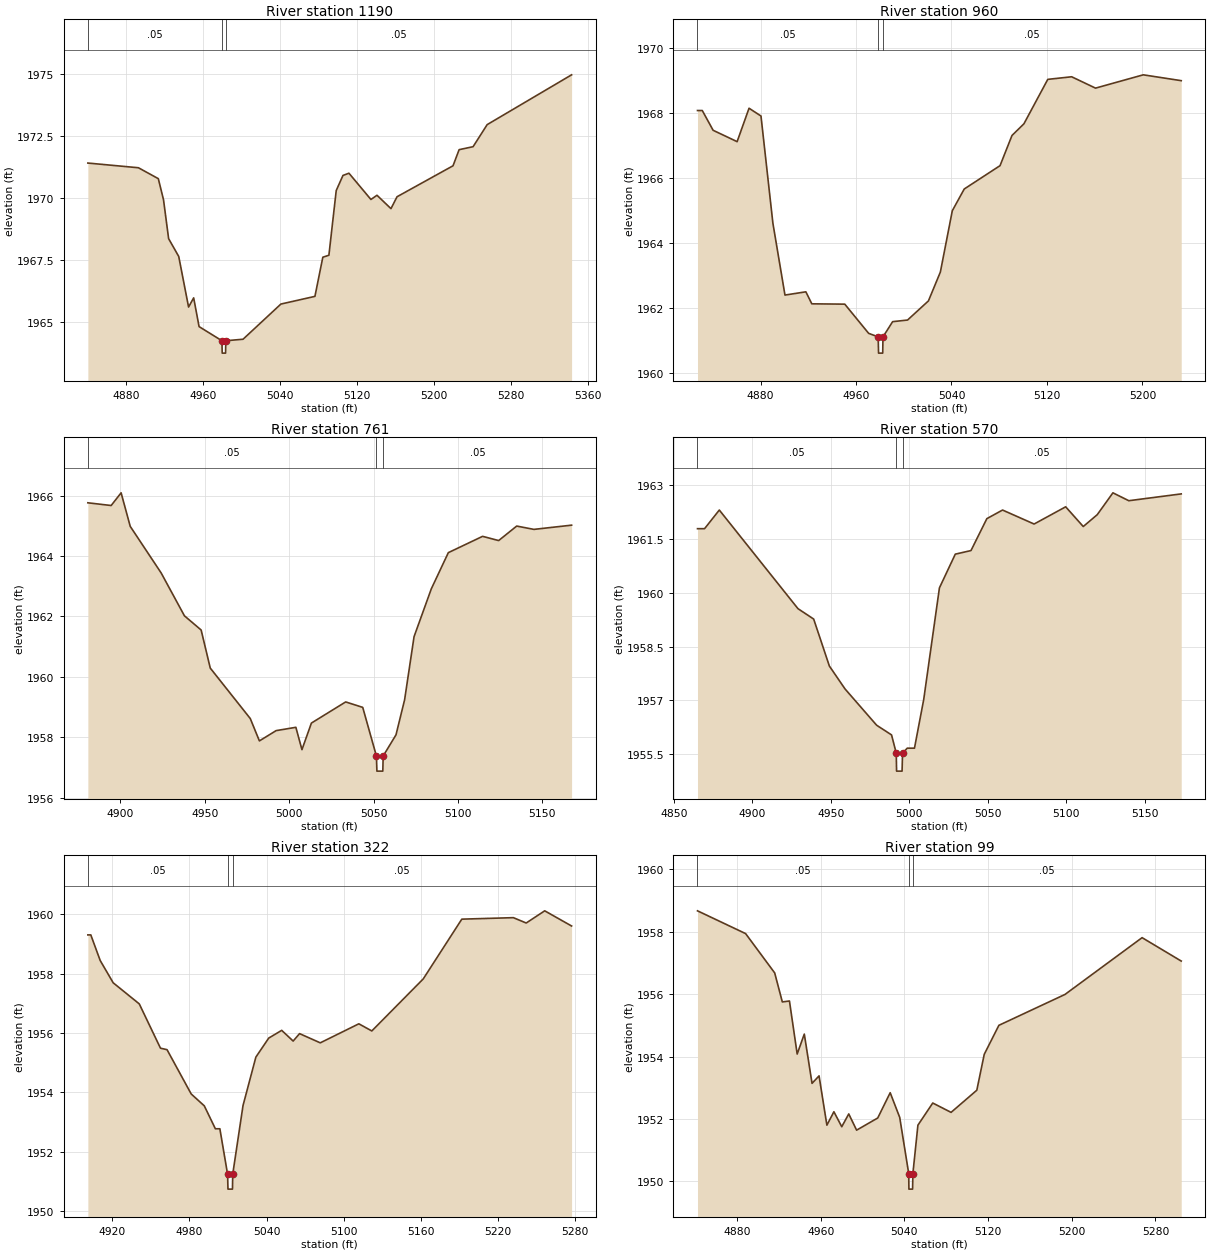
Type RM Length L Ch R = 1 ,1190    ,230,230,230
BEGIN DESCRIPTION:
Elm 01 61 1189.51
END DESCRIPTION:
XS GIS Cut Line= 3
      1580964.59       6771938.8      1581016.67      6772091.15
       1581223.7      6772361.98
#Sta/Elev= 30
  4840.7 1971.42  4893.2 1971.23  4913.8 1970.79  4919.2 1969.94  4924.5 1968.37
    4935 1967.65  4945.2 1965.61  4950.5 1965.98  4956.1 1964.82  4979.8 1964.25
  4980.1 1963.75  4983.6 1963.75  4983.8 1964.25  5001.7 1964.31    5041 1965.73
  5076.3 1966.04  5084.5 1967.62  5090.8  1967.7  5098.4 1970.31  5105.4 1970.92
  5111.6 1971.01  5134.4 1969.95  5140.7 1970.12  5155.2 1969.58  5161.5 1970.06
  5219.6 1971.31  5225.9 1971.96  5240.4 1972.08    5255 1972.97  5342.6 1974.98
#Mann= 3 ,-1 , 0
  4840.7     .05       0  4979.8     .03       0  4983.8     .05       0
Bank Sta=4979.8,4983.8
XS Rating Curve= 0 ,0
Exp/Cntr=0.3,0.1

Type RM Length L Ch R = 1 ,960     ,199,199,199
BEGIN DESCRIPTION:
Elm 01 61 960.44
END DESCRIPTION:
XS GIS Cut Line= 3
       1580856.3      6772064.91      1580844.58      6772238.06
      1580841.98       6772469.8
#Sta/Elev= 30
  4827.2 1968.08  4831.2 1968.08  4840.3 1967.47  4860.4 1967.12  4870.4 1968.15
  4880.4 1967.91  4890.4  1964.6  4900.5 1962.39    4918 1962.49    4923 1962.12
  4950.6 1962.11  4970.6 1961.21  4978.6  1961.1  4978.9  1960.6  4982.4  1960.6
  4982.6  1961.1  4990.7 1961.57  5003.2 1961.62  5020.7 1962.21  5030.7  1963.1
  5040.7 1964.99  5050.7 1965.66  5080.7 1966.38  5090.7 1967.31  5100.7 1967.67
  5120.7 1969.04  5140.7 1969.12  5160.7 1968.77  5200.7 1969.18  5232.5    1969
#Mann= 3 ,-1 , 0
  4827.2     .05       0  4978.6     .03       0  4982.6     .05       0
Bank Sta=4978.6,4982.6
XS Rating Curve= 0 ,0
Exp/Cntr=0.3,0.1

Type RM Length L Ch R = 1 ,761     ,191,191,191
BEGIN DESCRIPTION:
Elm 01 61 761.17
END DESCRIPTION:
XS GIS Cut Line= 3
      1580707.86      6772075.29      1580660.99      6772185.98
      1580633.65      6772350.01
#Sta/Elev= 30
  4880.8 1965.76  4894.6 1965.67  4900.5 1966.09  4905.9 1964.98  4924.2 1963.44
    4938 1962.02  4947.9 1961.55  4953.3 1960.29    4977 1958.62  4982.4 1957.88
  4992.3 1958.22    5004 1958.33  5007.6 1957.59  5013.2 1958.47  5033.5 1959.17
  5043.6 1958.99  5051.7 1957.38    5052 1956.88  5055.5 1956.88  5055.7 1957.38
  5063.3 1958.08  5068.4 1959.24    5074 1961.33  5084.2 1962.91  5094.3 1964.11
  5114.6 1964.65  5124.1 1964.51  5134.8 1964.99    5145 1964.88  5167.3 1965.02
#Mann= 3 ,-1 , 0
  4880.8     .05       0  5051.7     .05       0  5055.7     .05       0
Bank Sta=5051.7,5055.7
XS Rating Curve= 0 ,0
Exp/Cntr=0.3,0.1

Type RM Length L Ch R = 1 ,570     ,248,248,248
BEGIN DESCRIPTION:
Elm 01 61 570.04
END DESCRIPTION:
XS GIS Cut Line= 3
      1580506.04      6772044.08      1580499.53      6772182.07
      1580483.91       6772351.3
#Sta/Elev= 28
  4865.1 1961.79  4869.6 1961.79    4879 1962.31  4929.1 1959.56  4939.1 1959.27
  4949.1 1957.96  4959.1 1957.32  4979.2 1956.31  4988.7 1956.04  4991.7 1955.53
  4991.9 1955.03  4995.4 1955.03  4995.7 1955.53  4998.7 1955.67  5003.3 1955.67
  5009.2 1957.03  5019.2 1960.14  5029.3 1961.08  5039.3 1961.18  5049.4 1962.07
  5059.4 1962.31  5079.5 1961.92  5099.6  1962.4  5110.8 1961.85  5119.7 1962.18
  5129.7 1962.79  5139.8 1962.57  5173.2 1962.76
#Mann= 3 ,-1 , 0
  4865.1     .05       0  4991.7     .05       0  4995.7     .05       0
Bank Sta=4991.7,4995.7
XS Rating Curve= 0 ,0
Exp/Cntr=0.3,0.1

Type RM Length L Ch R = 1 ,322     ,223,223,223
BEGIN DESCRIPTION:
Elm 01 61 322.28
END DESCRIPTION:
XS GIS Cut Line= 3
       1580291.2       6771998.5      1580306.82      6772100.04
      1580321.13      6772373.23
#Sta/Elev= 30
    4901  1959.3  4903.3  1959.3  4910.6 1958.44  4920.7 1957.69    4941 1956.98
  4957.5 1955.49  4962.6 1955.44  4981.4 1953.95  4991.6 1953.55  5000.2 1952.78
  5003.7 1952.78  5009.7 1951.25    5010 1950.75  5013.5 1950.75  5013.7 1951.25
  5021.7 1953.56  5031.7 1955.19  5041.7 1955.83  5051.8 1956.09  5060.7 1955.73
  5065.7 1955.98  5081.8 1955.67  5111.8 1956.31  5121.9 1956.07  5161.9 1957.82
  5191.9 1959.83    5232 1959.88    5242  1959.7  5256.4 1960.11  5277.3  1959.6
#Mann= 3 ,-1 , 0
    4901     .05       0  5009.7     .05       0  5013.7     .05       0
Bank Sta=5009.7,5013.7
XS Rating Curve= 0 ,0
Exp/Cntr=0.3,0.1

Type RM Length L Ch R = 1 ,99      ,0,0,0
BEGIN DESCRIPTION:
Elm 01 61 960.178
END DESCRIPTION:
XS GIS Cut Line= 3
      1580229.59      6771988.04      1580112.91      6772094.28
      1580208.58      6772383.46
#Sta/Elev= 30
  4842.2 1958.67  4888.2 1957.94    4916 1956.68  4923.3 1955.75  4930.1 1955.78
  4937.5 1954.08  4944.3 1954.72  4951.7 1953.14  4958.4 1953.38  4965.9  1951.8
  4972.6 1952.23  4980.1 1951.75  4986.8 1952.16  4994.3 1951.64  5014.5 1952.03
  5026.4 1952.84  5035.5 1952.05  5044.1 1950.25  5044.3 1949.75  5047.8 1949.75
  5048.1 1950.25  5052.9  1951.8  5067.1 1952.51  5084.6 1952.21  5109.2 1952.92
  5116.3 1954.07  5130.3    1955  5193.5 1955.99  5267.2 1957.81  5304.6 1957.06
#Mann= 3 ,-1 , 0
  4842.2     .05       0  5044.1     .05       0  5048.1     .05       0
Bank Sta=5044.1,5048.1
XS Rating Curve= 0 ,0
Exp/Cntr=0.3,0.1

Chan Stop Cuts=-1
Use User Specified Reach Order=0
Composite Channel Slope=5