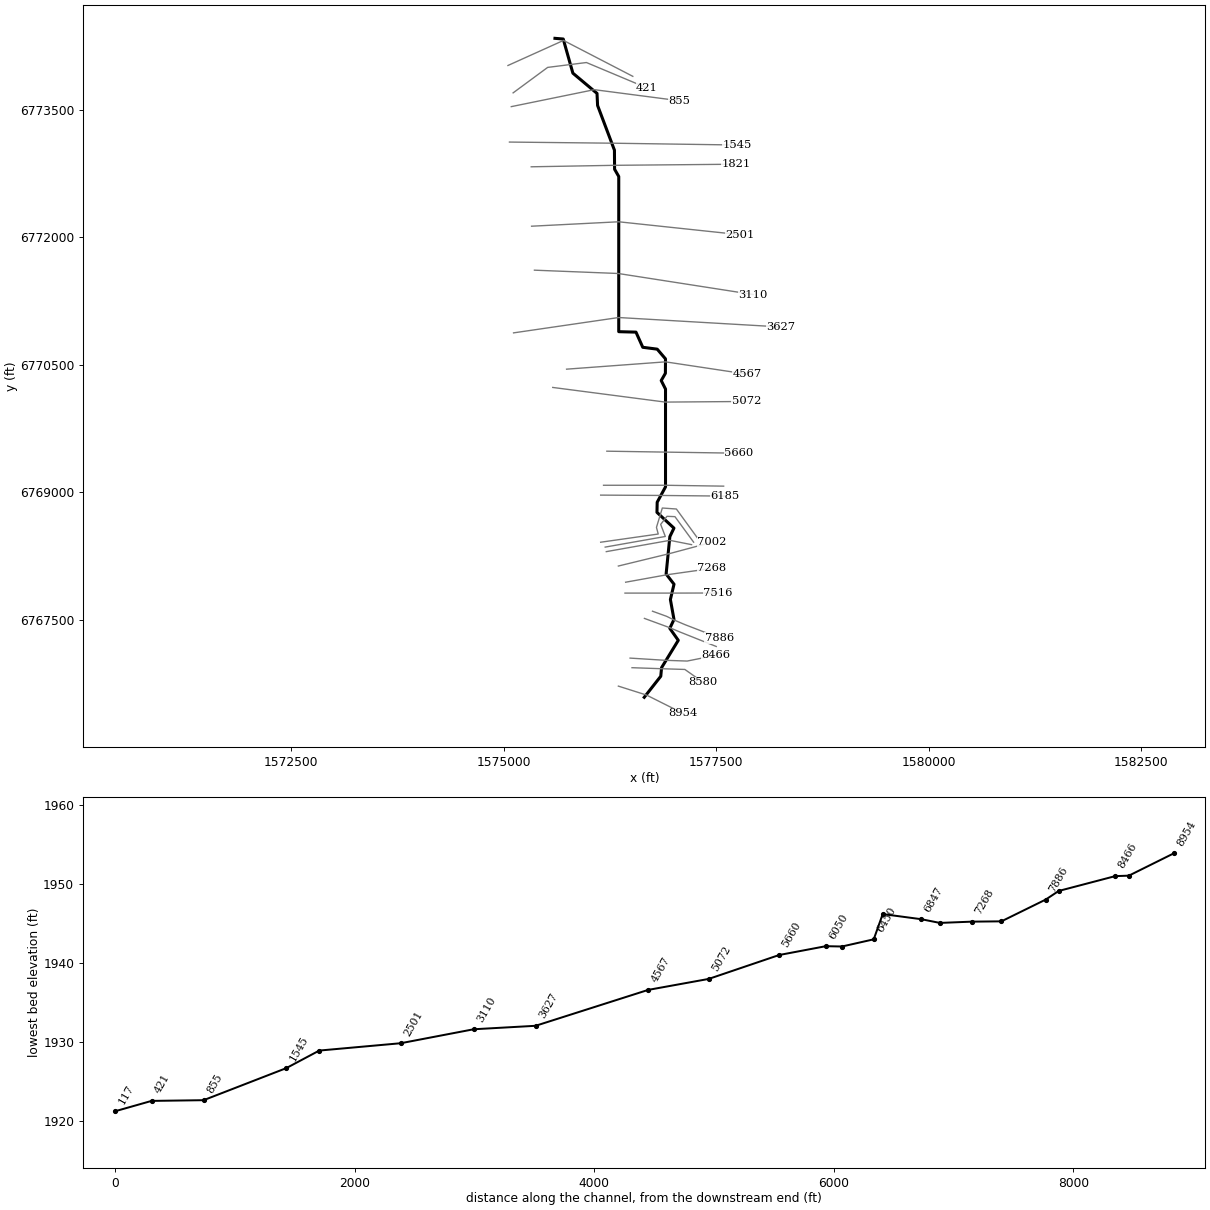
--- Elm 01 62.prj (project) ---

Proj Title=Elm 01 62 Base Level Engineering
Current Plan=p01
Default Exp/Contr=0.3,0.1
English Units
Geom File=g01
Flow File=f01
Plan File=p01
Y Axis Title=Elevation
X Axis Title(PF)=Main Channel Distance
X Axis Title(XS)=Station
BEGIN DESCRIPTION:
Elm 01 62
END DESCRIPTION:
DSS Export Rating Curves= 0
DSS Export Rating Curve Sorted= 0
DSS Export Volume Flow Curves= 0
DXF OffsetX= 0
DXF OffsetY= 0
DXF ScaleX= 1
DXF ScaleY= 10

--- Elm 01 62.p01 (plan) ---

Plan Title=Multiple Run
Short Identifier=Multiple
Geom File=g01
Flow File=f01
Subcritical Flow
K Sum by GR= 0
Std Step Tol= 0.01
Critical Tol= 0.01
Num of Std Step Trials= 20
Max Error Tol= 0.3
Flow Tol Ratio= 0.001
Split Flow NTrial= 30
Split Flow Tol= 0.02
Split Flow Ratio= 0.02
Log Output Level= 0
Friction Slope Method= 1
Unsteady Friction Slope Method= 2
Unsteady Bridges Friction Slope Method= 1
Parabolic Critical Depth
Global Vel Dist=  1 , 1 , 1
Global Log Level= 0
CheckData=True
Encroach Param= -1, 0, 0, 0
BEGIN DESCRIPTION:
Multiple Run
END DESCRIPTION:

--- Elm 01 62.f01 (steady flow) ---

Flow Title=Multiple
Program Version=4.10
Number of Profiles= 7
Profile Names=10-year,25-year,50-year,1pct_min,100-year,1pct_plu,500-year
River Rch & RM=Elm 01 62,Reach-1         ,8954
     144     191     228     169     271     374     388
River Rch & RM=Elm 01 62,Reach-1         ,5072
     176     237     285     213     342     470     496
River Rch & RM=Elm 01 62,Reach-1         ,3627
     256     352     431     326     523     719     780
River Rch & RM=Elm 01 62,Reach-1         ,3110
     256     352     431     326     523     719     780
Boundary for River Rch & Prof#=Elm 01 62,Reach-1         , 1
Up Type= 0
Dn Type= 3
Dn Slope=0.001
Boundary for River Rch & Prof#=Elm 01 62,Reach-1         , 2
Up Type= 0
Dn Type= 3
Dn Slope=0.001
Boundary for River Rch & Prof#=Elm 01 62,Reach-1         , 3
Up Type= 0
Dn Type= 3
Dn Slope=0.001
Boundary for River Rch & Prof#=Elm 01 62,Reach-1         , 4
Up Type= 0
Dn Type= 3
Dn Slope=0.001
Boundary for River Rch & Prof#=Elm 01 62,Reach-1         , 5
Up Type= 0
Dn Type= 3
Dn Slope=0.001
Boundary for River Rch & Prof#=Elm 01 62,Reach-1         , 6
Up Type= 0
Dn Type= 3
Dn Slope=0.001
Boundary for River Rch & Prof#=Elm 01 62,Reach-1         , 7
Up Type= 0
Dn Type= 3
Dn Slope=0.001
DSS Import GetInterval= 0
DSS Import GetPeak= 0
DSS Import FillOption= 0

--- Elm 01 62.g01 (geometry) ---

Geom Title=Existing Conditions

River Reach=Elm 01 62,Reach-1
Reach XY= 30
      1576655.00      6766588.00      1576849.46      6766835.58
      1576858.83      6766936.41      1577055.37      6767258.20
      1576955.61      6767398.63      1577004.83      6767503.41
      1576962.59      6767737.99      1577005.05      6767918.01
      1576912.33      6768037.90      1576956.24      6768477.50
      1577004.47      6768577.53      1576804.68      6768762.88
      1576807.23      6768882.07      1576905.21      6769062.91
      1576905.19      6770213.09      1576854.60      6770313.00
      1576903.76      6770398.50      1576905.05      6770568.02
      1576807.46      6770682.54      1576637.78      6770704.24
      1576557.74      6770882.66      1576355.00      6770888.00
      1576355.20      6772713.08      1576306.22      6772798.50
      1576304.48      6773022.78      1576106.23      6773548.51
      1576099.54      6773690.46      1575815.76      6773928.32
      1575702.14      6774330.20      1575605.00      6774338.00

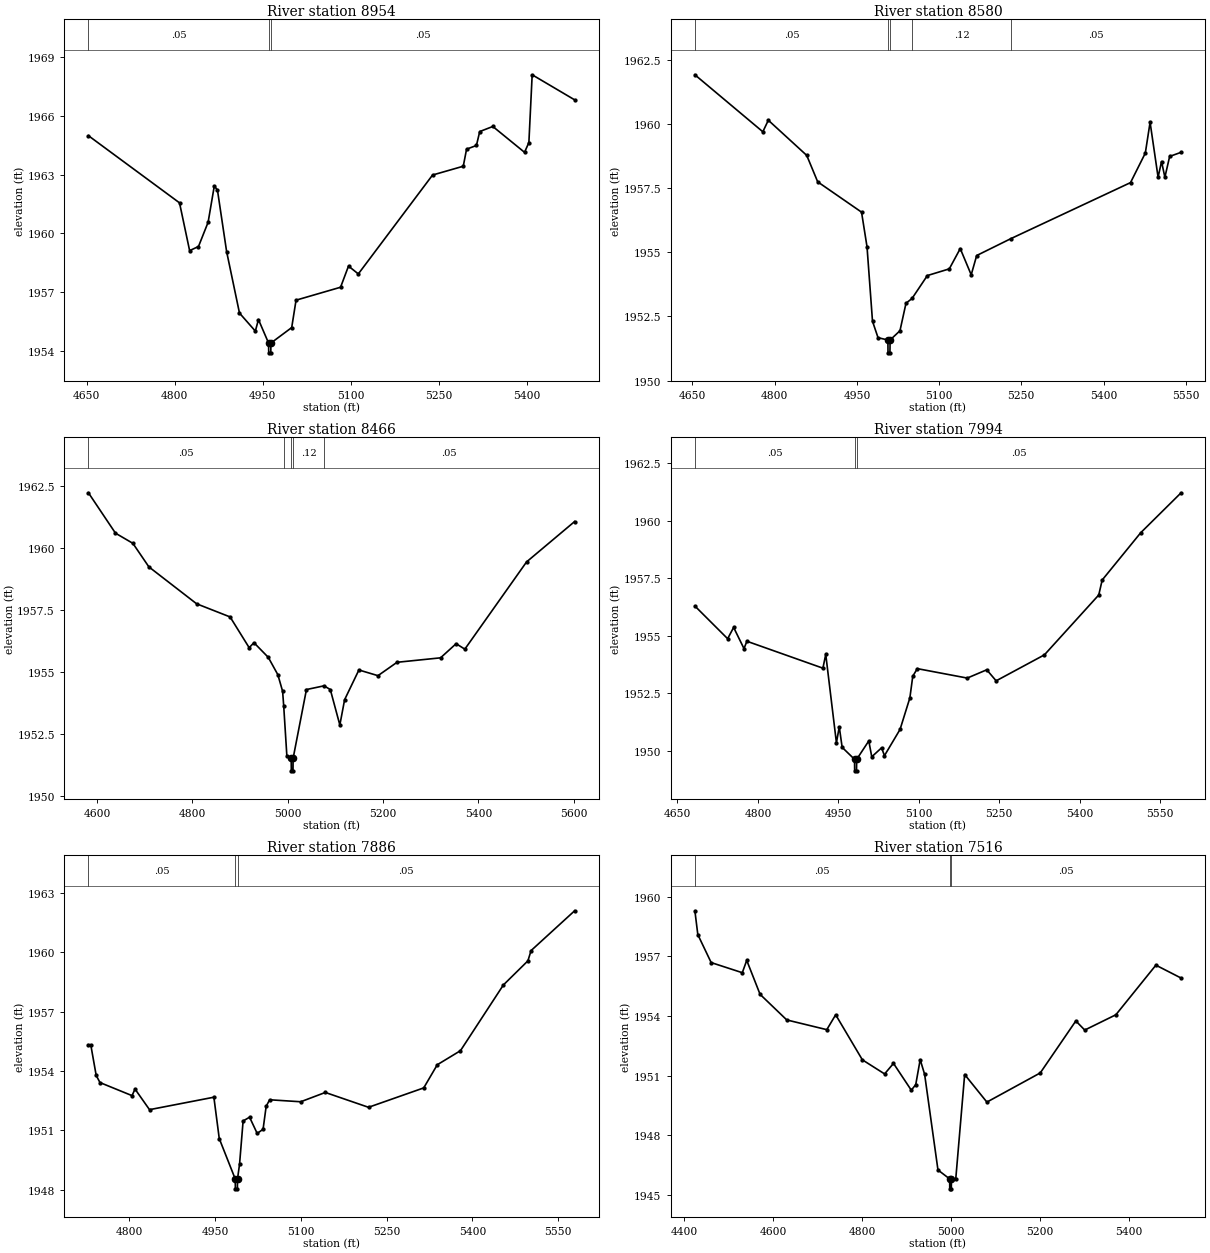
Type RM Length L Ch R = 1,8954,374,374,374
BEGIN DESCRIPTION:
Elm 01 62 8503.765
END DESCRIPTION:
XS GIS Cut Line= 3
      1576350.73      6766719.42      1576681.31      6766614.61
      1577111.21      6766398.86
#Sta/Elev= 30
  4653.2 1964.99  4808.3 1961.56  4825.5 1959.12  4840.6 1959.33  4857.0 1960.57
  4867.5 1962.42  4872.9 1962.21  4888.5 1959.07  4910.4 1955.93  4937.4 1955.01
  4942.7 1955.60  4959.9 1954.40  4960.2 1953.90  4963.7 1953.90  4963.9 1954.40
  4999.3 1955.19  5006.7 1956.59  5082.5 1957.25  5096.0 1958.33  5112.7 1957.93
  5239.1 1962.98  5291.4 1963.43  5297.0 1964.30  5313.8 1964.49  5319.4 1965.20
  5341.7 1965.46  5395.7 1964.14  5403.1 1964.64  5408.7 1968.10  5481.0 1966.82
#Mann=3,-1,0
  4653.2    0.05       0  4959.9    0.03       0  4963.9    0.05       0
Bank Sta=4959.9,4963.9
Exp/Cntr=0.3,0.1

Type RM Length L Ch R = 1,8580,114,114,114
BEGIN DESCRIPTION:
Elm 01 62 8579.89
END DESCRIPTION:
XS GIS Cut Line= 4
      1576511.05      6766936.06      1576856.11      6766924.13
      1577132.80      6766915.45      1577349.32      6766762.48
#Sta/Elev= 30
  4654.4 1961.91  4778.4 1959.69  4788.4 1960.14  4858.5 1958.77  4878.5 1957.74
  4958.5 1956.56  4968.5 1955.21  4978.5 1952.31  4988.6 1951.67  5006.6 1951.58
  5006.8 1951.08  5010.3 1951.08  5010.6 1951.58  5028.6 1951.94  5039.6 1953.01
  5050.7 1953.20  5078.6 1954.09  5118.6 1954.35  5138.6 1955.14  5158.6 1954.12
  5168.6 1954.87  5231.2 1955.53  5449.3 1957.71  5476.3 1958.86  5485.0 1960.06
  5499.6 1957.92  5505.9 1958.53  5512.0 1957.92  5520.7 1958.73  5541.6 1958.89
#Mann=5,-1,0
  4654.4    0.05       0  5006.6    0.05       0  5010.6    0.05       0
  5050.7    0.12       0  5231.2    0.05       0
Bank Sta=5006.6,5010.6
Exp/Cntr=0.3,0.1

Type RM Length L Ch R = 1,8466,472,472,472
BEGIN DESCRIPTION:
Elm 01 62 8466.12
END DESCRIPTION:
XS GIS Cut Line= 4
      1576488.31      6767048.91      1576904.93      6767022.87
      1577159.93      6767014.19      1577500.90      6767082.38
#Sta/Elev= 30
  4581.7 1962.24  4638.5 1960.61  4675.0 1960.20  4708.6 1959.25  4808.8 1957.76
  4879.0 1957.23  4919.0 1955.99  4929.1 1956.19  4959.1 1955.60  4979.2 1954.90
  4989.2 1954.23  4991.5 1953.64  4998.1 1951.63  5007.2 1951.52  5007.5 1951.02
  5011.0 1951.02  5011.2 1951.52  5039.2 1954.30  5076.1 1954.45  5089.3 1954.30
  5109.3 1952.87  5119.3 1953.89  5149.3 1955.09  5189.3 1954.86  5229.3 1955.40
  5320.6 1955.58  5353.3 1956.15  5371.6 1955.93  5501.1 1959.45  5602.0 1961.08
#Mann=5,-1,0
  4581.7    0.05       0  4991.5    0.12       0  5007.2    0.07       0
  5011.2    0.12       0  5076.1    0.05       0
Bank Sta=5007.2,5011.2
Exp/Cntr=0.3,0.1

Type RM Length L Ch R = 1,7994,108,108,108
BEGIN DESCRIPTION:
Elm 01 62 7993.75
END DESCRIPTION:
XS GIS Cut Line= 4
      1576657.14      6767515.72      1576955.35      6767406.33
      1577072.54      6767356.85      1577501.73      6767185.70
#Sta/Elev= 30
  4682.5 1956.30  4743.6 1954.88  4754.8 1955.37  4774.1 1954.45  4779.5 1954.77
  4921.3 1953.60  4926.6 1954.20  4946.5 1950.36  4951.8 1951.05  4957.2 1950.16
  4980.3 1949.64  4980.5 1949.14  4984.0 1949.14  4984.3 1949.64  5006.9 1950.44
  5012.4 1949.75  5030.7 1950.14  5036.1 1949.80  5065.2 1950.94  5083.5 1952.31
  5088.9 1953.25  5097.4 1953.58  5190.5 1953.17  5226.9 1953.53  5244.4 1953.05
  5334.5 1954.18  5435.8 1956.78  5442.2 1957.43  5513.9 1959.48  5589.4 1961.22
#Mann=3,-1,0
  4682.5    0.05       0  4980.3    0.05       0  4984.3    0.05       0
Bank Sta=4980.3,4984.3
Exp/Cntr=0.3,0.1

Type RM Length L Ch R = 1,7886,370,370,370
BEGIN DESCRIPTION:
Elm 01 62 7886.14
END DESCRIPTION:
XS GIS Cut Line= 5
      1576752.22      6767600.34      1576917.59      6767540.45
      1577004.83      6767497.48      1577136.34      6767441.49
      1577541.26      6767285.75
#Sta/Elev= 30
  4728.9 1955.33  4733.0 1955.33  4742.5 1953.78  4749.1 1953.42  4805.1 1952.76
  4810.4 1953.09  4835.7 1952.05  4948.2 1952.68  4957.6 1950.59  4985.5 1948.55
  4985.8 1948.05  4989.3 1948.05  4989.5 1948.55  4993.1 1949.30  4999.3 1951.48
  5010.6 1951.67  5023.9 1950.85  5034.2 1951.06  5039.6 1952.22  5045.7 1952.55
  5100.0 1952.45  5143.0 1952.92  5218.5 1952.17  5315.0 1953.15  5338.7 1954.32
  5379.2 1955.03  5454.2 1958.35  5497.1 1959.57  5502.7 1960.09  5578.8 1962.10
#Mann=3,-1,0
  4728.9    0.05       0  4985.5    0.05       0  4989.5    0.05       0
Bank Sta=4985.5,4989.5
Exp/Cntr=0.3,0.1

Type RM Length L Ch R = 1,7516,248,248,248
BEGIN DESCRIPTION:
Elm 01 62 7516.09
END DESCRIPTION:
XS GIS Cut Line= 3
      1576428.41      6767813.45      1577006.57      6767813.45
      1577521.71      6767814.75
#Sta/Elev= 30
  4423.6 1959.30  4430.2 1958.10  4460.2 1956.69  4530.2 1956.18  4540.2 1956.80
  4570.2 1955.09  4630.2 1953.80  4720.2 1953.31  4740.2 1954.06  4800.2 1951.79
  4850.2 1951.08  4870.2 1951.61  4910.2 1950.26  4920.2 1950.54  4930.2 1951.80
  4940.2 1951.06  4970.2 1946.24  4996.5 1945.79  4996.7 1945.29  5000.2 1945.29
  5000.5 1945.79  5010.2 1945.79  5030.2 1951.05  5080.2 1949.66  5200.2 1951.13
  5280.2 1953.75  5300.2 1953.29  5370.2 1954.06  5460.2 1956.56  5516.9 1955.91
#Mann=3,-1,0
  4423.6    0.05       0  4996.5    0.03       0  5000.5    0.05       0
Bank Sta=4996.5,5000.5
Exp/Cntr=0.3,0.1

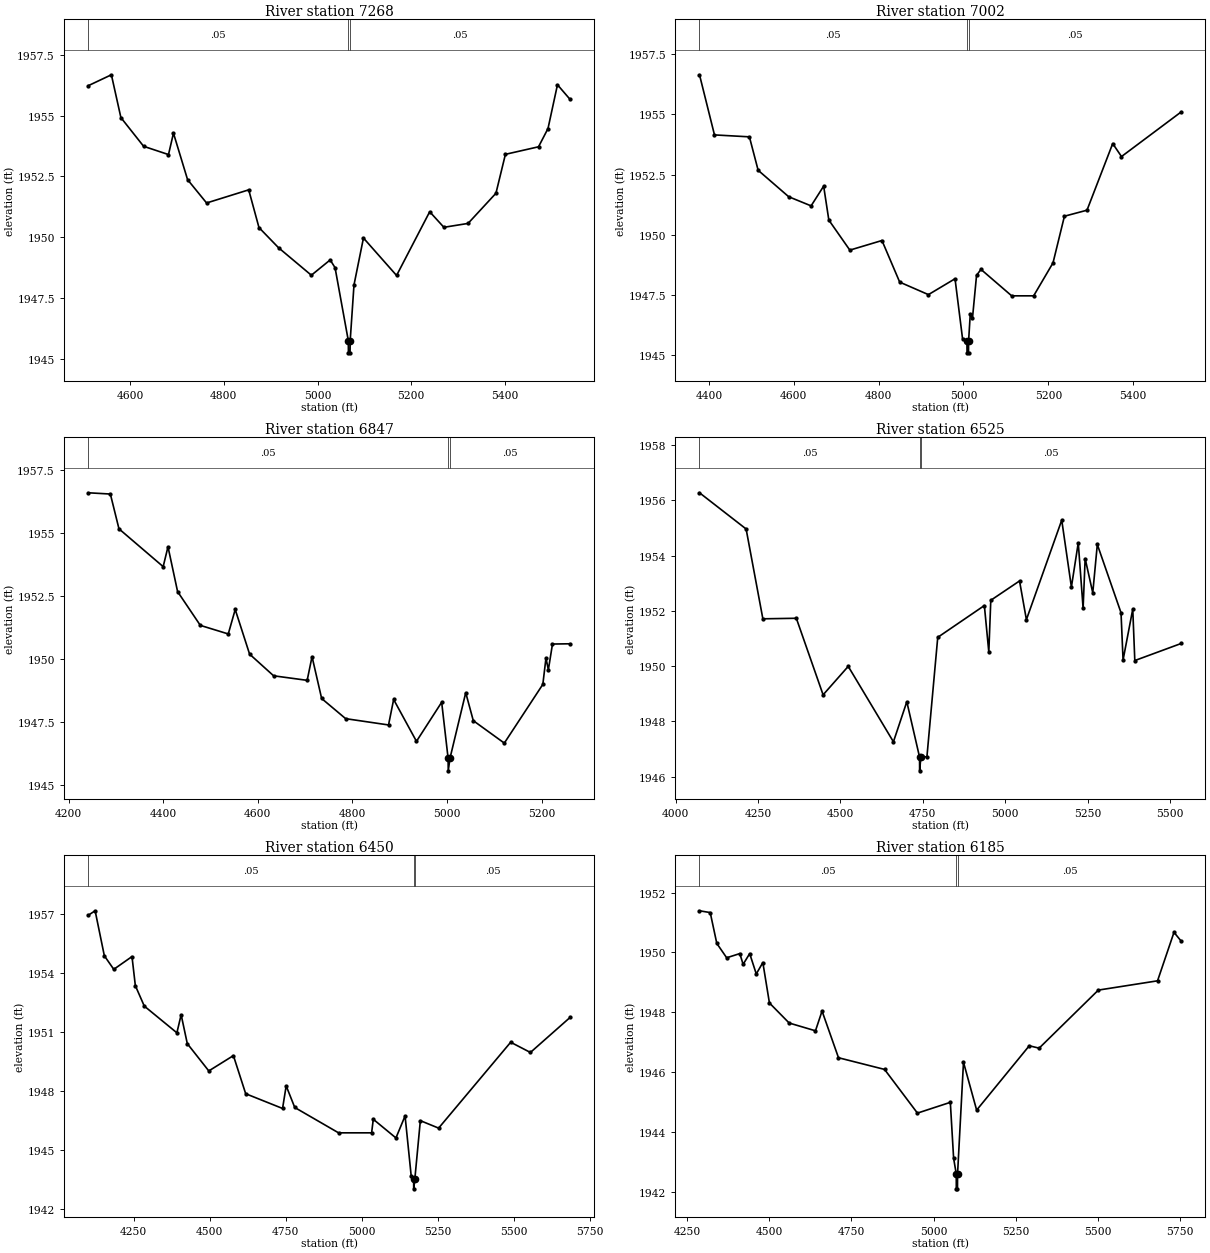
Type RM Length L Ch R = 1,7268,266,266,266
BEGIN DESCRIPTION:
Elm 01 62 7267.89
END DESCRIPTION:
XS GIS Cut Line= 3
      1576436.30      6767941.49      1576919.33      6768028.73
      1577451.58      6768104.02
#Sta/Elev= 30
  4510.5 1956.23  4560.0 1956.68  4580.3 1954.92  4628.8 1953.74  4681.9 1953.40
  4692.5 1954.28  4722.6 1952.37  4763.2 1951.41  4853.1 1951.95  4875.0 1950.40
  4916.8 1949.57  4986.8 1948.44  5027.0 1949.07  5037.4 1948.75  5065.7 1945.75
  5065.9 1945.25  5069.4 1945.25  5069.7 1945.75  5077.8 1948.04  5098.0 1949.97
  5168.7 1948.43  5239.4 1951.05  5269.7 1950.41  5321.3 1950.57  5380.8 1951.81
  5401.0 1953.41  5471.7 1953.72  5491.9 1954.47  5512.1 1956.27  5538.9 1955.67
#Mann=3,-1,0
  4510.5    0.05       0  5065.7    0.03       0  5069.7    0.05       0
Bank Sta=5065.7,5069.7
Exp/Cntr=0.3,0.1

Type RM Length L Ch R = 1,7002,155,155,155
BEGIN DESCRIPTION:
Elm 01 62 7002.45
END DESCRIPTION:
XS GIS Cut Line= 3
      1576350.72      6768131.80      1576956.22      6768278.94
      1577451.17      6768411.45
#Sta/Elev= 30
  4377.9 1956.65  4413.2 1954.15  4495.5 1954.07  4516.1 1952.68  4588.1 1951.58
  4640.9 1951.20  4670.5 1952.02  4682.7 1950.61  4732.2 1949.36  4807.9 1949.76
  4849.7 1948.03  4917.4 1947.51  4980.1 1948.17  4997.8 1945.68  5008.1 1945.59
  5008.4 1945.09  5011.9 1945.09  5012.1 1945.59  5016.0 1946.70  5021.2 1946.53
  5030.8 1948.31  5041.2 1948.56  5113.6 1947.46  5165.4 1947.46  5211.0 1948.83
  5237.9 1950.77  5291.1 1951.02  5351.7 1953.79  5372.4 1953.25  5513.4 1955.11
#Mann=3,-1,0
  4377.9    0.05       0  5008.1    0.05       0  5012.1    0.05       0
Bank Sta=5008.1,5012.1
Exp/Cntr=0.3,0.1

Type RM Length L Ch R = 1,6847,322,322,322
BEGIN DESCRIPTION:
Elm 01 62 6847.29
END DESCRIPTION:
XS GIS Cut Line= 3
      1576208.82      6768301.08      1576956.22      6768433.89
      1577211.36      6768383.38
#Sta/Elev= 30
  4241.1 1956.59  4288.0 1956.54  4306.2 1955.16  4399.7 1953.66  4409.9 1954.45
  4430.2 1952.67  4478.3 1951.33  4537.4 1950.99  4552.1 1951.96  4582.5 1950.19
  4633.3 1949.33  4704.3 1949.15  4714.6 1950.09  4734.9 1948.43  4785.7 1947.63
  4876.4 1947.38  4887.2 1948.39  4935.5 1946.73  4988.8 1948.28  5002.4 1946.06
  5002.7 1945.56  5006.4 1946.06  5039.7 1948.66  5055.7 1947.55  5121.3 1946.66
  5202.8 1948.99  5209.4 1950.03  5214.5 1949.57  5223.2 1950.59  5260.3 1950.60
#Mann=3,-1,0
  4241.1    0.05       0  5002.4    0.05       0  5006.4    0.05       0
Bank Sta=5002.4,5006.4
Exp/Cntr=0.3,0.1

Type RM Length L Ch R = 1,6525,75,75,75
BEGIN DESCRIPTION:
Elm 01 62 6525.41
END DESCRIPTION:
XS GIS Cut Line= 6
      1576195.78      6768354.46      1576902.84      6768479.46
      1576848.15      6768621.39      1576922.37      6768716.44
      1577016.12      6768712.54      1577235.73      6768412.36
#Sta/Elev= 30
  4072.5 1956.27  4213.9 1954.96  4264.7 1951.71  4366.2 1951.73  4447.4 1948.96
  4523.6 1949.99  4660.7 1947.26  4701.3 1948.71  4739.9 1946.71  4740.2 1946.21
  4743.9 1946.71  4762.3 1946.72  4795.1 1951.04  4936.5 1952.19  4950.0 1950.51
  4956.0 1952.38  5043.2 1953.08  5064.0 1951.68  5171.2 1955.28  5200.5 1952.86
  5221.3 1954.46  5236.0 1952.09  5242.2 1953.89  5265.3 1952.65  5279.1 1954.40
  5351.0 1951.93  5357.2 1950.22  5386.6 1952.06  5392.8 1950.20  5533.9 1950.82
#Mann=3,-1,0
  4072.5    0.05       0  4739.9    0.05       0  4743.9    0.05       0
Bank Sta=4739.9,4743.9
Exp/Cntr=0.3,0.1

Type RM Length L Ch R = 1,6450,265,265,265
BEGIN DESCRIPTION:
Elm 01 62 6449.55
END DESCRIPTION:
XS GIS Cut Line= 6
      1576142.41      6768411.75      1576819.50      6768508.11
      1576798.67      6768586.24      1576867.68      6768814.10
      1577033.05      6768802.38      1577276.56      6768467.71
#Sta/Elev= 30
  4100.1 1956.93  4122.9 1957.16  4153.2 1954.87  4184.2 1954.18  4244.1 1954.83
  4255.1 1953.35  4284.5 1952.31  4391.7 1950.95  4405.7 1951.87  4425.9 1950.40
  4496.6 1949.01  4577.5 1949.79  4617.9 1947.85  4739.1 1947.10  4751.0 1948.25
  4779.2 1947.15  4923.2 1945.86  5031.9 1945.86  5037.4 1946.55  5111.9 1945.60
  5141.9 1946.72  5162.0 1943.67  5170.0 1943.51  5170.3 1943.01  5174.0 1943.51
  5192.1 1946.48  5252.2 1946.10  5489.1 1950.47  5554.0 1949.95  5684.2 1951.73
#Mann=3,-1,0
  4100.1    0.05       0  5170.0    0.05       0  5174.0    0.05       0
Bank Sta=5170,5174
Exp/Cntr=0.3,0.1

Type RM Length L Ch R = 1,6185,135,135,135
BEGIN DESCRIPTION:
Elm 01 62 6185.23
END DESCRIPTION:
XS GIS Cut Line= 3
      1576142.42      6768965.79      1576854.66      6768961.89
      1577607.27      6768954.07
#Sta/Elev= 30
  4288.2 1951.39  4320.8 1951.33  4340.8 1950.30  4370.8 1949.82  4410.8 1949.96
  4420.8 1949.60  4440.8 1949.96  4460.8 1949.28  4480.8 1949.66  4500.8 1948.31
  4560.8 1947.64  4640.8 1947.38  4660.8 1948.04  4710.8 1946.48  4850.8 1946.09
  4950.8 1944.63  5050.8 1944.99  5060.8 1943.12  5068.8 1942.60  5069.0 1942.10
  5072.5 1942.10  5072.8 1942.60  5090.8 1946.33  5130.8 1944.73  5290.8 1946.88
  5320.8 1946.80  5500.8 1948.74  5680.8 1949.05  5730.8 1950.67  5753.1 1950.37
#Mann=3,-1,0
  4288.2    0.05       0  5068.8    0.05       0  5072.8    0.05       0
Bank Sta=5068.8,5072.8
Exp/Cntr=0.3,0.1

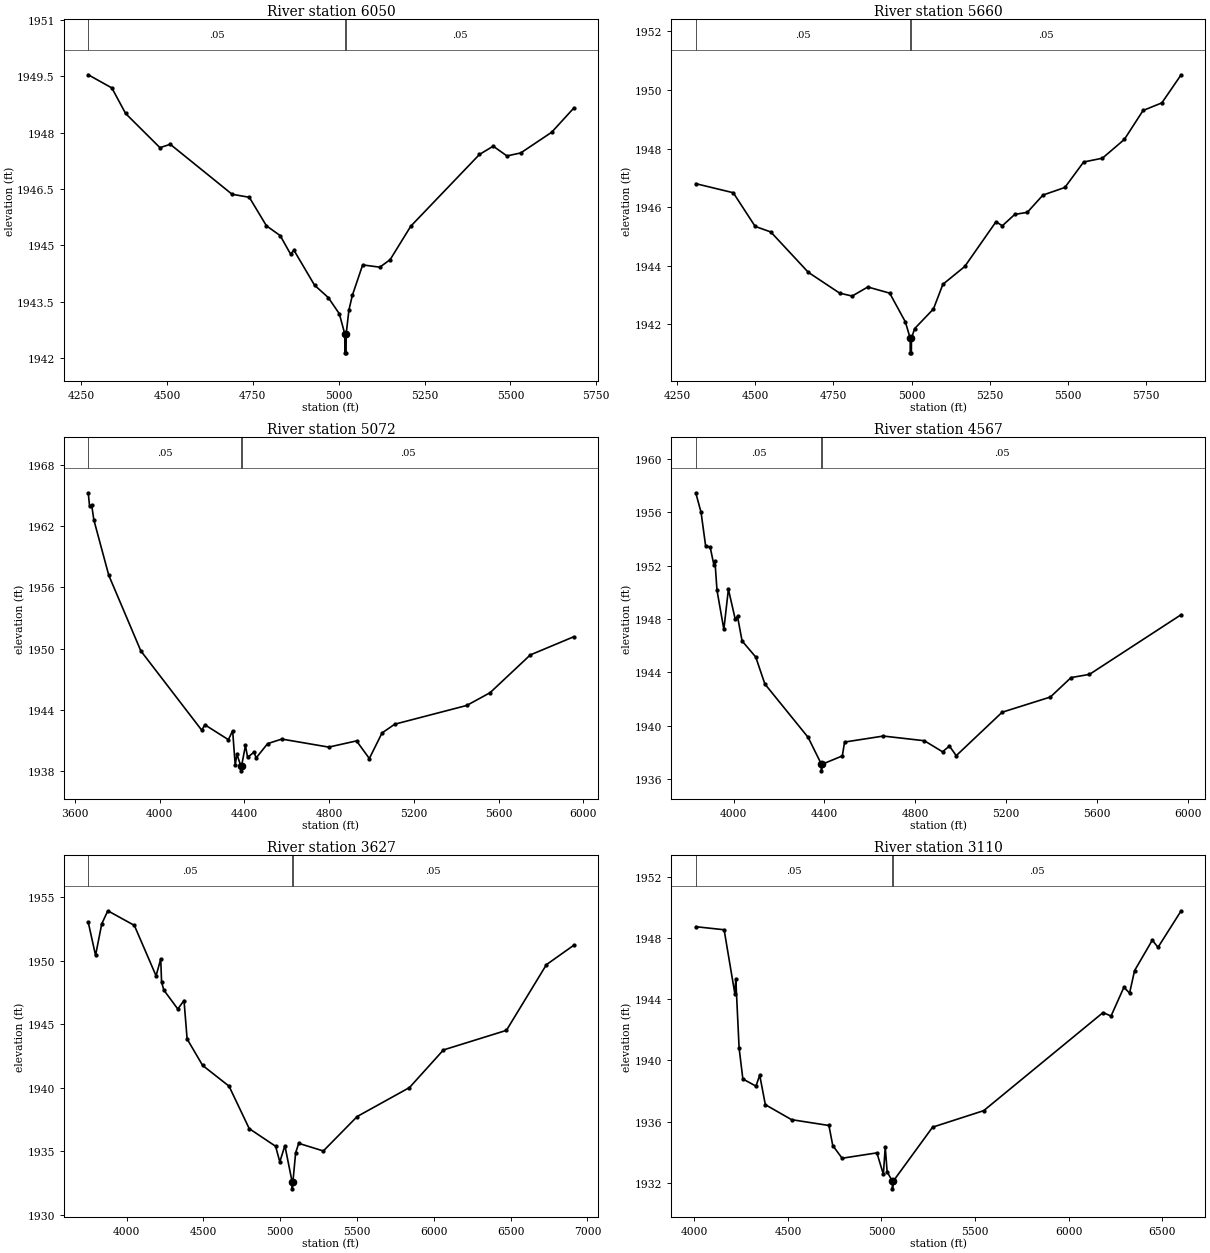
Type RM Length L Ch R = 1,6050,390,390,390
BEGIN DESCRIPTION:
Elm 01 62 6050.09
END DESCRIPTION:
XS GIS Cut Line= 3
      1576176.31      6769081.68      1576904.14      6769081.68
      1577589.03      6769071.26
#Sta/Elev= 30
  4271.1 1949.54  4339.8 1949.19  4379.8 1948.51  4479.8 1947.60  4509.8 1947.69
  4689.8 1946.36  4739.8 1946.28  4789.8 1945.52  4829.8 1945.26  4859.8 1944.77
  4869.8 1944.87  4929.8 1943.94  4969.8 1943.61  5001.9 1943.18  5017.8 1942.64
  5018.0 1942.14  5021.5 1942.14  5021.8 1942.64  5029.8 1943.28  5039.8 1943.67
  5069.8 1944.48  5119.8 1944.42  5149.8 1944.62  5209.8 1945.51  5409.8 1947.42
  5449.8 1947.64  5489.8 1947.38  5529.9 1947.46  5619.9 1948.01  5683.9 1948.65
#Mann=3,-1,0
  4271.1    0.05       0  5017.8    0.03       0  5021.8    0.05       0
Bank Sta=5017.8,5021.8
Exp/Cntr=0.3,0.1

Type RM Length L Ch R = 1,5660,588,588,588
BEGIN DESCRIPTION:
Elm 01 62 5660.1
END DESCRIPTION:
XS GIS Cut Line= 3
      1576215.09      6769482.50      1576905.15      6769471.65
      1577766.71      6769458.63
#Sta/Elev= 30
  4309.8 1946.80  4429.7 1946.49  4499.7 1945.34  4549.7 1945.15  4669.8 1943.77
  4769.8 1943.06  4809.8 1942.96  4859.8 1943.27  4929.8 1943.06  4979.8 1942.08
  4995.4 1941.52  4995.6 1941.02  4999.1 1941.02  4999.4 1941.52  5009.8 1941.85
  5069.8 1942.52  5099.8 1943.36  5169.8 1943.97  5269.8 1945.50  5289.8 1945.36
  5329.8 1945.75  5369.8 1945.82  5419.8 1946.41  5489.9 1946.67  5549.9 1947.54
  5609.9 1947.67  5679.9 1948.31  5739.9 1949.30  5799.9 1949.56  5861.6 1950.52
#Mann=3,-1,0
  4309.8    0.05       0  4995.4    0.03       0  4999.4    0.05       0
Bank Sta=4995.4,4999.4
Exp/Cntr=0.3,0.1

Type RM Length L Ch R = 1,5072,505,505,505
BEGIN DESCRIPTION:
Elm 01 62 5071.72
END DESCRIPTION:
XS GIS Cut Line= 3
      1575578.87      6770232.21      1576901.97      6770059.90
      1577859.67      6770067.28
#Sta/Elev= 30
  3662.5 1965.29  3668.7 1963.98  3678.8 1964.07  3688.9 1962.63  3759.4 1957.19
  3910.7 1949.77  4198.3 1941.98  4213.2 1942.51  4324.2 1941.05  4344.3 1941.92
  4356.4 1938.57  4364.5 1939.61  4382.7 1938.49  4382.9 1937.99  4386.7 1938.49
  4404.8 1940.48  4414.9 1939.32  4445.2 1939.82  4455.3 1939.26  4509.5 1940.66
  4576.3 1941.11  4798.1 1940.32  4929.2 1940.93  4989.7 1939.20  5049.8 1941.71
  5109.8 1942.57  5449.8 1944.41  5559.8 1945.66  5749.8 1949.37  5954.5 1951.15
#Mann=3,-1,0
  3662.5    0.05       0  4382.7   0.035       0  4386.7    0.05       0
Bank Sta=4382.7,4386.7
Exp/Cntr=0.3,0.1

Type RM Length L Ch R = 1,4567,940,940,940
BEGIN DESCRIPTION:
Elm 01 62 4567.29
END DESCRIPTION:
XS GIS Cut Line= 3
      1575741.66      6770447.06      1576904.78      6770533.14
      1577864.03      6770388.46
#Sta/Elev= 30
  3833.7 1957.47  3857.1 1956.00  3877.2 1953.48  3897.2 1953.39  3913.2 1952.08
  3918.2 1952.34  3927.3 1950.14  3957.4 1947.22  3977.4 1950.23  4007.5 1947.98
  4017.5 1948.19  4037.6 1946.35  4097.8 1945.14  4137.9 1943.12  4328.4 1939.11
  4386.6 1937.10  4386.8 1936.60  4390.6 1937.10  4478.8 1937.72  4488.8 1938.76
  4659.3 1939.21  4839.8 1938.86  4920.0 1938.03  4950.1 1938.46  4980.2 1937.74
  5182.3 1941.00  5394.6 1942.14  5485.6 1943.60  5566.6 1943.84  5970.1 1948.32
#Mann=3,-1,0
  3833.7    0.05       0  4386.6    0.05       0  4390.6    0.05       0
Bank Sta=4386.6,4390.6
Exp/Cntr=0.3,0.1

Type RM Length L Ch R = 1,3627,517,517,517
BEGIN DESCRIPTION:
Elm 01 62 3626.83
END DESCRIPTION:
XS GIS Cut Line= 3
      1575118.02      6770873.95      1576354.17      6771054.51
      1578261.98      6770943.51
#Sta/Elev= 30
  3749.9 1953.03  3797.4 1950.42  3837.8 1952.90  3877.4 1953.93  4050.0 1952.78
  4191.5 1948.81  4221.8 1950.14  4227.3 1948.32  4242.0 1947.69  4333.0 1946.20
  4373.4 1946.87  4393.6 1943.84  4494.7 1941.76  4666.5 1940.13  4797.9 1936.79
  4969.7 1935.40  4997.1 1934.17  5030.1 1935.45  5078.1 1932.55  5078.4 1932.05
  5082.1 1932.55  5100.2 1934.89  5120.2 1935.63  5280.5 1935.03  5500.8 1937.74
  5841.4 1940.02  6062.5 1942.98  6472.5 1944.52  6732.9 1949.69  6910.2 1951.21
#Mann=3,-1,0
  3749.9    0.05       0  5078.1    0.05       0  5082.1    0.05       0
Bank Sta=5078.1,5082.1
Exp/Cntr=0.3,0.1

Type RM Length L Ch R = 1,3110,609,609,609
BEGIN DESCRIPTION:
Elm 01 62 3109.77
END DESCRIPTION:
XS GIS Cut Line= 3
      1575363.48      6771611.37      1576348.76      6771572.31
      1577937.25      6771324.92
#Sta/Elev= 30
  4007.6 1948.74  4159.2 1948.54  4216.6 1944.36  4221.6 1945.32  4239.3 1940.81
  4259.3 1938.79  4329.4 1938.32  4349.4 1939.04  4379.4 1937.11  4519.5 1936.13
  4719.2 1935.75  4739.7 1934.44  4789.7 1933.61  4975.5 1933.96  5010.1 1932.56
  5020.2 1934.34  5030.3 1932.72  5058.4 1932.11  5058.7 1931.61  5062.9 1932.11
  5273.2 1935.64  5546.5 1936.72  6184.1 1943.13  6226.7 1942.90  6295.4 1944.78
  6325.8 1944.40  6352.4 1945.87  6447.2 1947.86  6477.6 1947.39  6601.3 1949.78
#Mann=3,-1,0
  4007.6    0.05       0  5058.4    0.05       0  5062.9    0.05       0
Bank Sta=5058.4,5062.9
Exp/Cntr=0.3,0.1

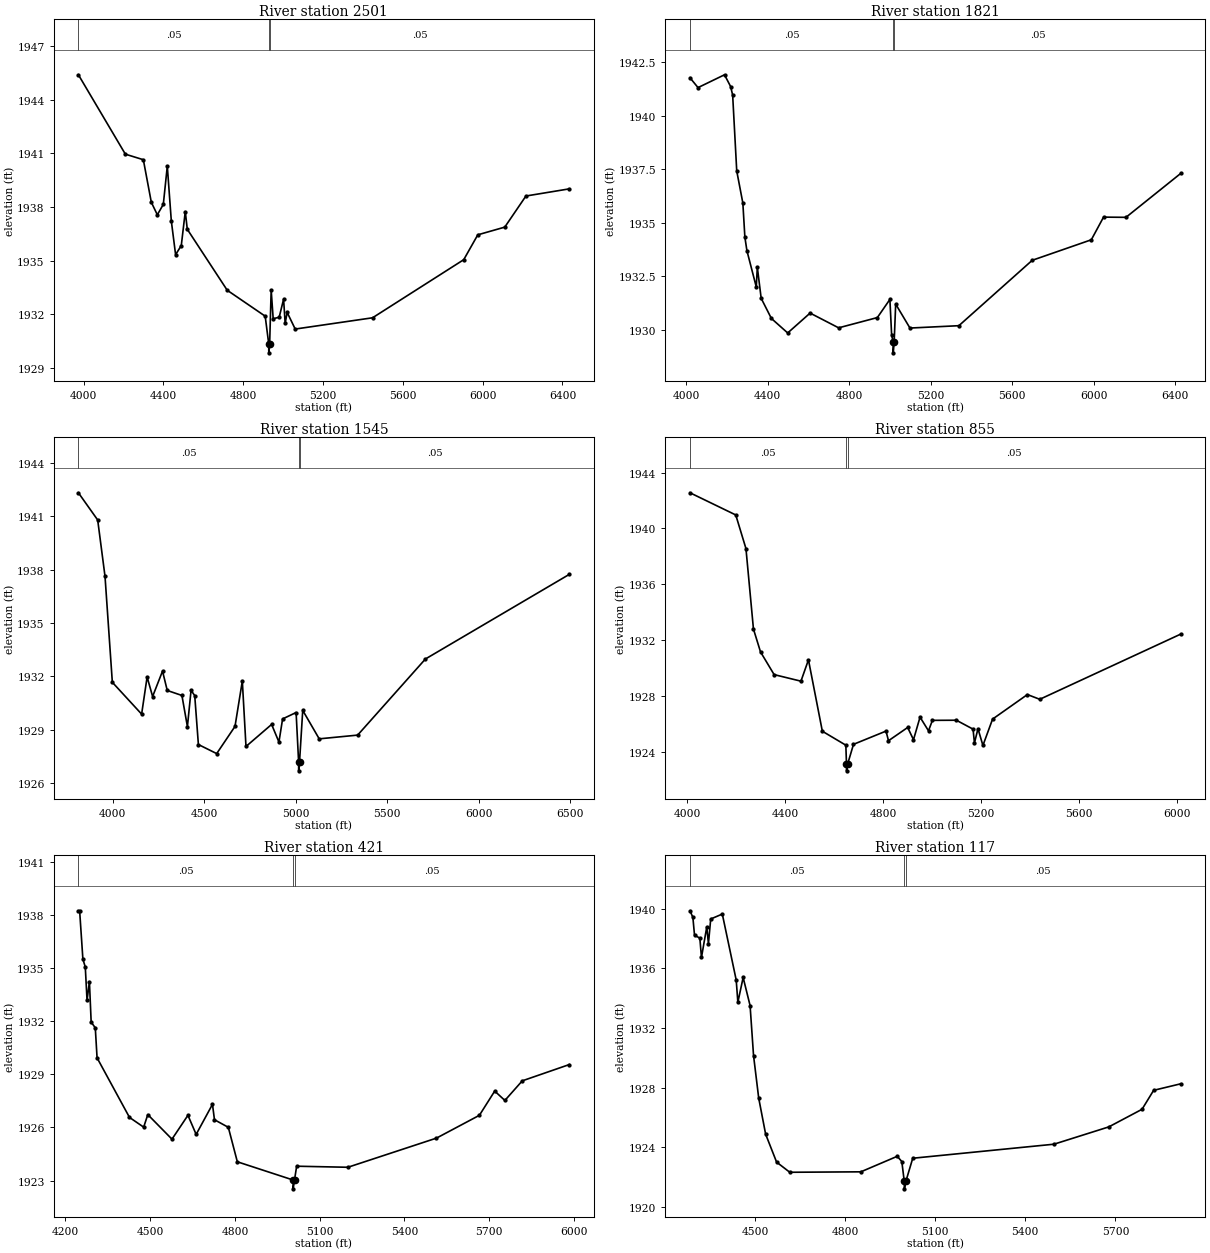
Type RM Length L Ch R = 1,2501,680,680,680
BEGIN DESCRIPTION:
Elm 01 62 2500.67
END DESCRIPTION:
XS GIS Cut Line= 3
      1575329.95      6772128.44      1576354.25      6772180.52
      1577781.07      6772028.73
#Sta/Elev= 30
  3973.5 1945.39  4208.9 1940.95  4299.0 1940.64  4339.0 1938.26  4369.1 1937.56
  4399.1 1938.14  4419.1 1940.28  4439.2 1937.22  4460.7 1935.33  4489.2 1935.84
  4509.2 1937.74  4519.3 1936.75  4719.5 1933.34  4909.8 1931.89  4927.5 1930.34
  4927.8 1929.84  4932.1 1930.34  4939.8 1933.35  4949.8 1931.75  4979.9 1931.83
  5002.0 1932.84  5009.9 1931.49  5020.0 1932.10  5060.2 1931.17  5447.9 1931.80
  5905.0 1935.05  5975.4 1936.44  6110.6 1936.87  6216.7 1938.61  6434.0 1939.01
#Mann=3,-1,0
  3973.5    0.05       0  4927.5    0.05       0  4932.1    0.05       0
Bank Sta=4927.5,4932.1
Exp/Cntr=0.3,0.1

Type RM Length L Ch R = 1,1821,276,276,276
BEGIN DESCRIPTION:
Elm 01 62 1821.01
END DESCRIPTION:
XS GIS Cut Line= 3
      1575325.61      6772827.23      1576306.51      6772844.59
      1577734.50      6772857.61
#Sta/Elev= 30
  4019.6 1941.78  4059.0 1941.32  4189.0 1941.92  4219.0 1941.37  4229.0 1940.97
  4249.0 1937.42  4279.0 1935.92  4289.0 1934.32  4299.0 1933.69  4345.0 1931.99
  4350.0 1932.92  4369.0 1931.46  4419.0 1930.52  4499.1 1929.84  4609.1 1930.77
  4749.1 1930.08  4939.1 1930.56  5000.7 1931.41  5009.1 1929.76  5016.6 1929.41
  5017.0 1928.91  5021.6 1929.41  5029.1 1931.19  5099.1 1930.07  5339.2 1930.18
  5699.2 1933.24  5989.2 1934.20  6049.2 1935.26  6159.2 1935.25  6428.7 1937.31
#Mann=3,-1,0
  4019.6    0.05       0  5016.6    0.03       0  5021.6    0.05       0
Bank Sta=5016.6,5021.6
Exp/Cntr=0.3,0.1

Type RM Length L Ch R = 1,1545,690,690,690
BEGIN DESCRIPTION:
Elm 01 62 1545.08
END DESCRIPTION:
XS GIS Cut Line= 3
      1575069.58      6773118.02      1576258.77      6773105.00
      1577750.95      6773083.31
#Sta/Elev= 30
  3812.6 1942.32  3918.0 1940.79  3958.0 1937.62  3998.0 1931.66  4158.0 1929.87
  4188.0 1931.96  4218.0 1930.86  4272.2 1932.29  4298.0 1931.20  4378.1 1930.92
  4408.1 1929.17  4428.1 1931.21  4448.1 1930.91  4468.1 1928.16  4568.1 1927.65
  4668.1 1929.18  4708.1 1931.73  4728.1 1928.05  4868.1 1929.29  4908.1 1928.30
  4928.1 1929.60  5001.9 1929.96  5015.6 1927.18  5015.9 1926.68  5020.6 1927.18
  5038.1 1930.08  5128.1 1928.48  5338.1 1928.69  5708.2 1932.97  6494.2 1937.73
#Mann=3,-1,0
  3812.6    0.05       0  5015.6    0.03       0  5020.6    0.05       0
Bank Sta=5015.6,5020.6
Exp/Cntr=0.3,0.1

Type RM Length L Ch R = 1,855,434,434,434
BEGIN DESCRIPTION:
Elm 01 62 855.14
END DESCRIPTION:
XS GIS Cut Line= 3
      1575091.25      6773534.69      1576067.80      6773734.34
      1577066.10      6773604.13
#Sta/Elev= 30
  4011.0 1942.56  4197.8 1940.97  4239.4 1938.56  4270.0 1932.79  4298.8 1931.15
  4354.4 1929.52  4463.9 1929.05  4494.5 1930.58  4551.2 1925.46  4647.1 1924.46
  4649.7 1923.12  4650.0 1922.62  4654.7 1923.12  4678.3 1924.52  4811.0 1925.47
  4821.2 1924.78  4899.5 1925.73  4923.2 1924.85  4949.9 1926.47  4984.5 1925.49
  5000.4 1926.24  5098.1 1926.25  5166.3 1925.61  5172.0 1924.62  5186.4 1925.64
  5206.6 1924.44  5246.0 1926.33  5388.1 1928.09  5438.6 1927.75  6014.5 1932.43
#Mann=3,-1,0
  4011.0    0.05       0  4649.7    0.05       0  4654.7    0.05       0
Bank Sta=4649.7,4654.7
Exp/Cntr=0.3,0.1

Type RM Length L Ch R = 1,421,304,304,304
BEGIN DESCRIPTION:
Mapping XS 52082509
END DESCRIPTION:
XS GIS Cut Line= 4
      1575112.88      6773696.71      1575519.14      6773996.20
      1575974.87      6774053.49      1576688.44      6773754.00
#Sta/Elev= 30
  4245.8 1938.26  4250.2 1938.26  4261.7 1935.52  4270.2 1935.08  4276.4 1933.19
  4284.8 1934.25  4291.0 1931.96  4305.6 1931.64  4311.9 1929.94  4426.7 1926.57
  4476.9 1926.02  4491.5 1926.73  4577.1 1925.34  4633.6 1926.69  4662.7 1925.61
  4720.5 1927.31  4727.5 1926.44  4776.6 1926.01  4808.5 1924.06  5005.8 1923.03
  5006.2 1922.53  5010.9 1923.03  5018.5 1923.81  5199.9 1923.75  5513.6 1925.40
  5665.5 1926.69  5719.7 1928.06  5755.7 1927.53  5817.3 1928.64  5983.7 1929.56
#Mann=3,-1,0
  4245.8    0.05       0  5005.8    0.05       0  5010.9    0.05       0
Bank Sta=5005.8,5010.9
Exp/Cntr=0.3,0.1

Type RM Length L Ch R = 1,117,0,0,0
BEGIN DESCRIPTION:
Elm 01 62 2441.261
END DESCRIPTION:
XS GIS Cut Line= 3
      1575052.10      6774018.64      1575705.20      6774313.32
      1576520.40      6773891.22
#Sta/Elev= 30
  4283.5 1939.85  4293.1 1939.41  4298.6 1938.21  4316.3 1938.02  4321.7 1936.72
  4339.4 1938.77  4344.9 1937.64  4352.5 1939.30  4391.1 1939.63  4437.4 1935.21
  4442.9 1933.72  4460.5 1935.38  4483.6 1933.50  4495.1 1930.15  4512.3 1927.30
  4535.4 1924.88  4571.9 1923.01  4615.8 1922.33  4852.5 1922.36  4973.6 1923.40
  4988.8 1923.05  4997.0 1921.72  4997.4 1921.22  5002.3 1921.72  5025.2 1923.27
  5495.3 1924.21  5678.0 1925.37  5788.7 1926.55  5827.3 1927.82  5918.0 1928.26
#Mann=3,-1,0
  4283.5    0.05       0  4997.0    0.05       0  5002.3    0.05       0
Bank Sta=4997,5002.3
Exp/Cntr=0.3,0.1

Chan Stop Cuts=-1