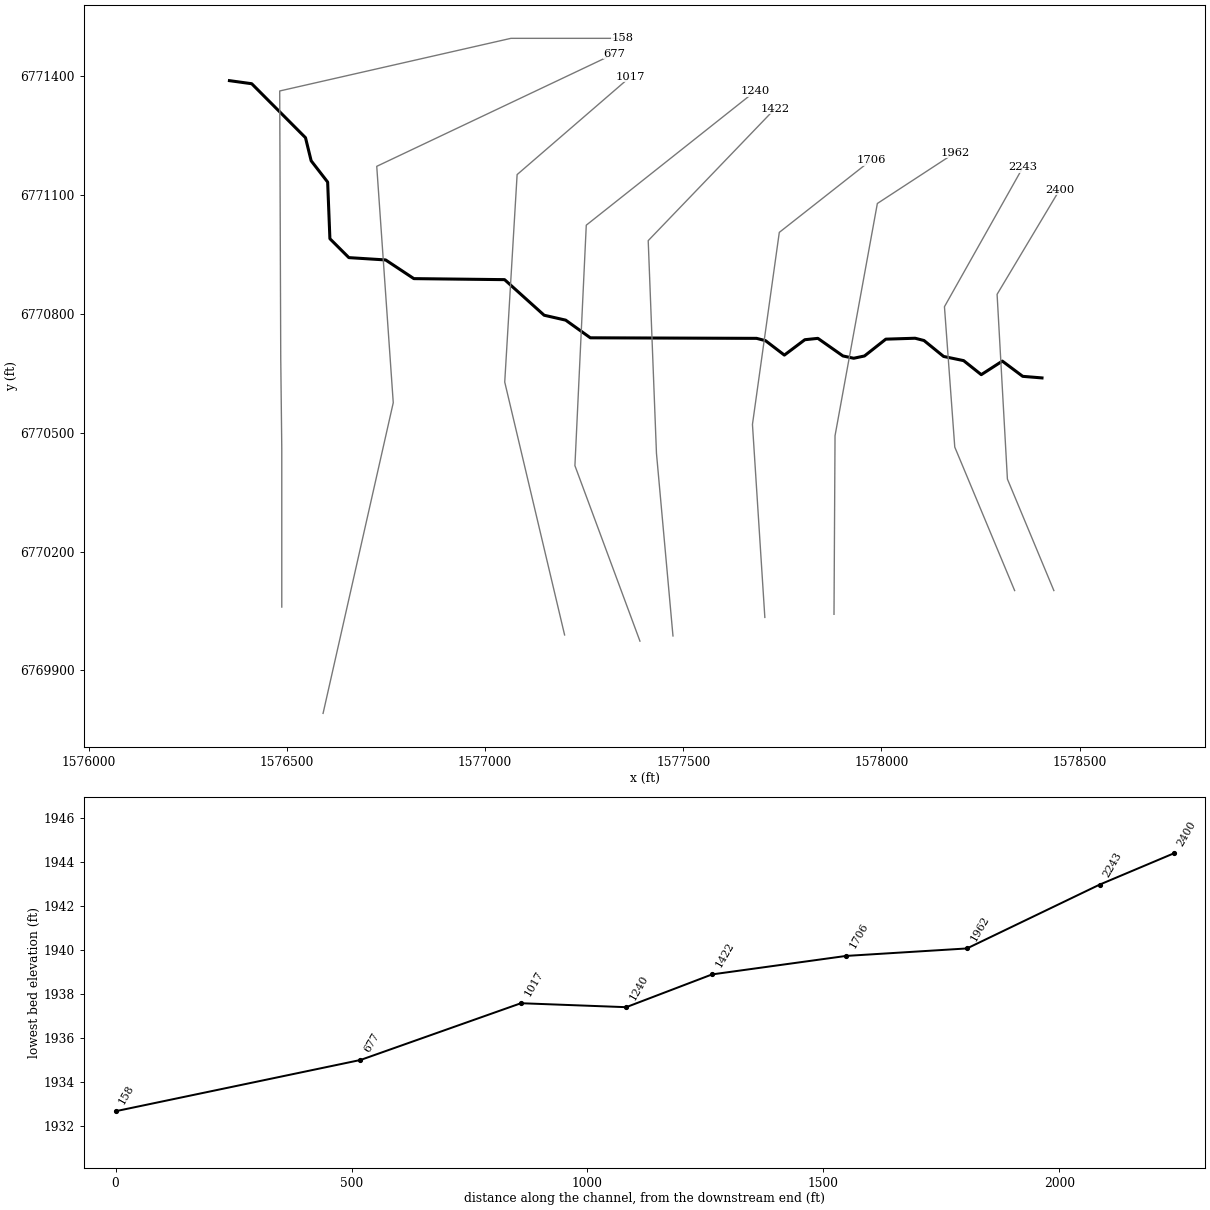
--- Elm 01 64.prj (project) ---

Proj Title=Elm 01 64 Base Level Engineering
Current Plan=p01
Default Exp/Contr=0.3,0.1
English Units
Geom File=g01
Flow File=f01
Plan File=p01
BEGIN DESCRIPTION:
Elm 01 64
END DESCRIPTION:

--- Elm 01 64.p01 (plan) ---

Plan Title=Multiple Run
Short Identifier=Multiple
Geom File=g01
Flow File=f01
Subcritical Flow
K Sum by GR= 0
Std Step Tol= 0.01
Critical Tol= 0.01
Num of Std Step Trials= 20
Max Error Tol= 0.3
Flow Tol Ratio= 0.001
Split Flow NTrial= 30
Split Flow Tol= 0.02
Split Flow Ratio= 0.02
Log Output Level= 0
Friction Slope Method= 1
Unsteady Friction Slope Method= 2
Unsteady Bridges Friction Slope Method= 1
Parabolic Critical Depth
Global Vel Dist=  1 , 1 , 1
Global Log Level= 0
CheckData=True
Encroach Param= -1, 0, 0, 0
BEGIN DESCRIPTION:
Multiple Run
END DESCRIPTION:

--- Elm 01 64.f01 (steady flow) ---

Flow Title=Multiple
Number of Profiles=7
Profile Names=10-year,25-year,50-year,1pct_min,100-year,1pct_plu,500-year
River Rch & RM= Elm 01 64,Reach-1,2400
      75      96     111      81     130     179     178
Boundary for River Rch & Prof#=Elm 01 64,Reach-1,1
Up Type=0
Dn Type=3
Dn Slope=0.001
Boundary for River Rch & Prof#=Elm 01 64,Reach-1,2
Up Type=0
Dn Type=3
Dn Slope=0.001
Boundary for River Rch & Prof#=Elm 01 64,Reach-1,3
Up Type=0
Dn Type=3
Dn Slope=0.001
Boundary for River Rch & Prof#=Elm 01 64,Reach-1,4
Up Type=0
Dn Type=3
Dn Slope=0.001
Boundary for River Rch & Prof#=Elm 01 64,Reach-1,5
Up Type=0
Dn Type=3
Dn Slope=0.001
Boundary for River Rch & Prof#=Elm 01 64,Reach-1,6
Up Type=0
Dn Type=3
Dn Slope=0.001
Boundary for River Rch & Prof#=Elm 01 64,Reach-1,7
Up Type=0
Dn Type=3
Dn Slope=0.001

--- Elm 01 64.g01 (geometry) ---

Geom Title=Existing Conditions

River Reach=Elm 01 64,Reach-1
Reach XY= 30
      1578405.00      6770638.00      1578356.36      6770641.98
      1578304.94      6770680.43      1578251.77      6770646.22
      1578207.30      6770681.63      1578156.75      6770692.16
      1578107.32      6770732.35      1578084.91      6770738.11
      1578010.97      6770735.81      1577957.18      6770693.38
      1577930.00      6770687.61      1577902.80      6770693.41
      1577839.59      6770737.83      1577806.64      6770734.39
      1577755.01      6770695.59      1577707.45      6770731.98
      1577685.02      6770737.82      1577265.50      6770739.20
      1577203.25      6770783.78      1577148.95      6770796.16
      1577049.14      6770885.94      1576820.22      6770888.52
      1576749.02      6770935.64      1576656.25      6770941.51
      1576608.44      6770989.23      1576602.75      6771132.07
      1576561.14      6771185.83      1576546.86      6771244.06
      1576411.21      6771380.24      1576355.00      6771388.00

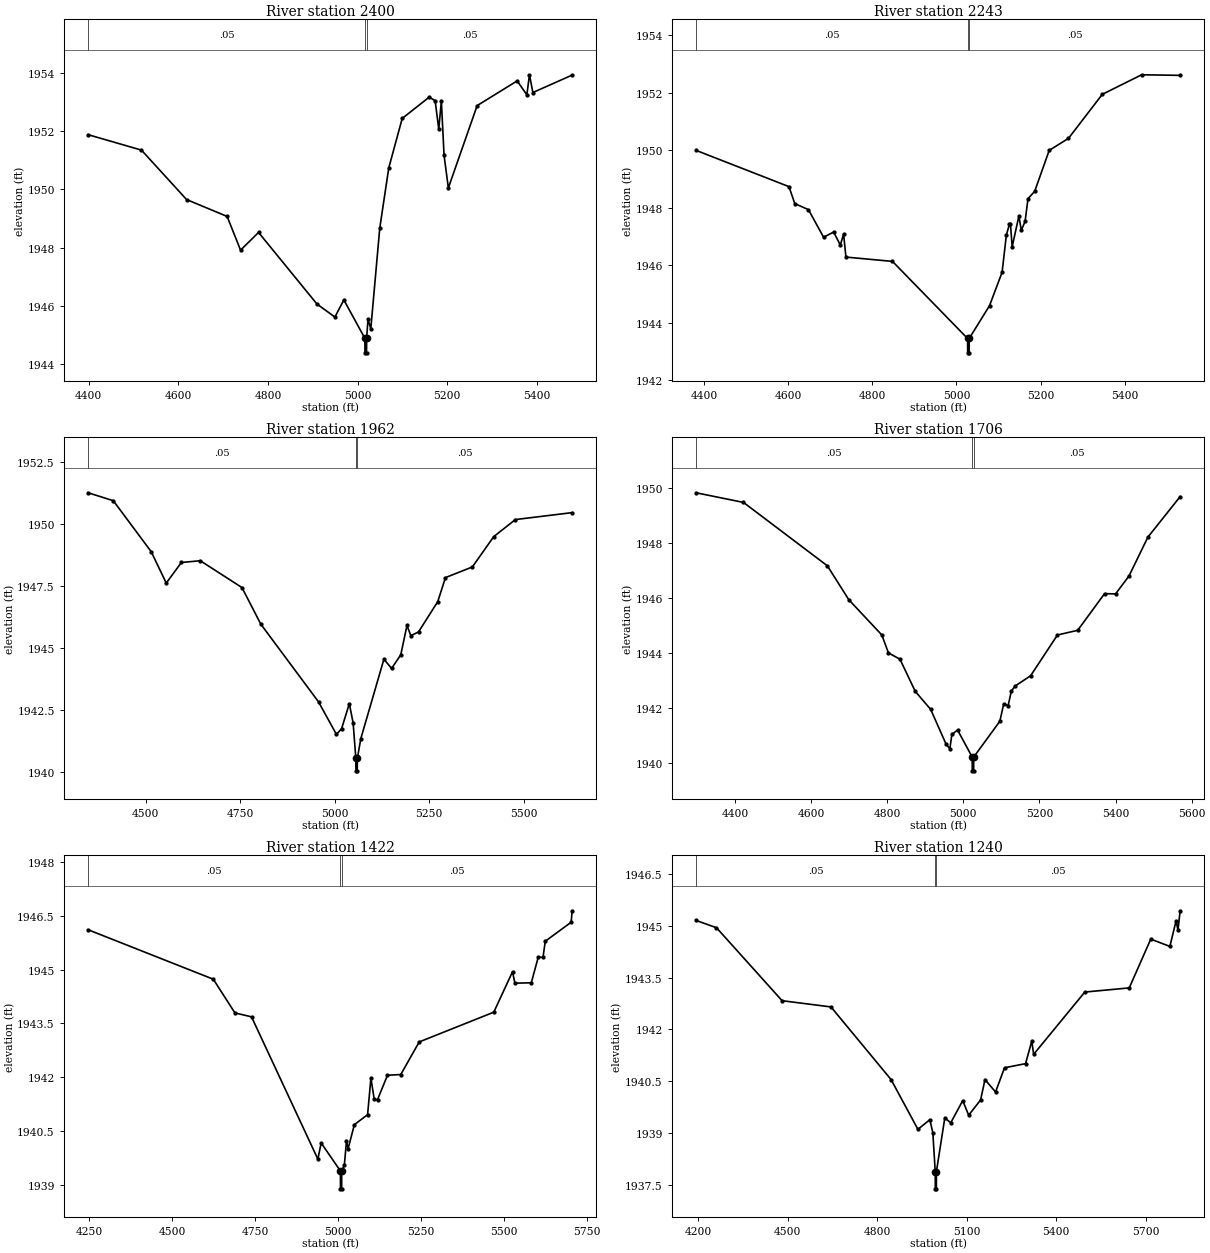
Type RM Length L Ch R = 1,2400,157,157,157
BEGIN DESCRIPTION:
Elm 01 64 2.0
END DESCRIPTION:
XS GIS Cut Line= 4
      1578434.93      6770101.54      1578317.75      6770382.77
      1578291.71      6770848.92      1578449.82      6771113.31
#Sta/Elev= 30
  4399.1 1951.88  4517.9 1951.35  4618.6 1949.65  4709.0 1949.07  4739.0 1947.91
  4779.1 1948.52  4909.3 1946.06  4949.4 1945.61  4969.4 1946.20  5016.2 1944.88
  5016.5 1944.38  5020.0 1944.38  5020.2 1944.88  5023.2 1945.53  5029.5 1945.21
  5049.5 1948.67  5069.6 1950.74  5099.6 1952.44  5159.7 1953.17  5173.0 1953.05
  5181.1 1952.07  5186.9 1953.04  5192.9 1951.17  5202.5 1950.05  5266.7 1952.88
  5356.0 1953.73  5377.6 1953.25  5383.4 1953.94  5391.0 1953.33  5478.7 1953.93
#Mann=3,-1,0
  4399.1    0.05       0  5016.2    0.05       0  5020.2    0.05       0
Bank Sta=5016.2,5020.2
Exp/Cntr=0.3,0.1

Type RM Length L Ch R = 1,2243,281,281,281
BEGIN DESCRIPTION:
Mapping XS 50de66b2
END DESCRIPTION:
XS GIS Cut Line= 4
      1578335.98      6770101.51      1578184.94      6770463.50
      1578158.90      6770817.67      1578356.81      6771169.23
#Sta/Elev= 30
  4380.9 1950.00  4601.7 1948.74  4615.5 1948.15  4648.0 1947.94  4684.0 1946.98
  4707.8 1947.16  4723.8 1946.71  4731.6 1947.09  4737.1 1946.29  4847.8 1946.14
  5026.3 1943.46  5026.6 1942.96  5030.1 1942.96  5030.3 1943.46  5078.5 1944.60
  5108.4 1945.76  5118.6 1947.06  5125.9 1947.43  5128.3 1947.43  5132.4 1946.65
  5148.4 1947.72  5154.1 1947.22  5163.1 1947.53  5170.0 1948.32  5186.0 1948.58
  5220.4 1950.00  5266.3 1950.42  5346.7 1951.95  5440.2 1952.63  5531.7 1952.61
#Mann=3,-1,0
  4380.9    0.05       0  5026.3    0.05       0  5030.3    0.05       0
Bank Sta=5026.3,5030.3
Exp/Cntr=0.3,0.1

Type RM Length L Ch R = 1,1962,256,256,256
BEGIN DESCRIPTION:
Mapping XS 92cfda98
END DESCRIPTION:
XS GIS Cut Line= 4
      1577880.25      6770041.64      1577882.85      6770492.14
      1577989.62      6771078.08      1578184.94      6771205.69
#Sta/Elev= 30
  4348.4 1951.27  4414.8 1950.95  4514.8 1948.90  4554.8 1947.63  4594.8 1948.46
  4644.8 1948.53  4754.8 1947.45  4804.9 1945.97  4957.3 1942.84  5004.6 1941.53
  5018.3 1941.76  5038.7 1942.77  5048.8 1941.99  5055.9 1940.56  5056.1 1940.06
  5059.6 1940.06  5059.9 1940.56  5069.1 1941.36  5130.1 1944.56  5150.5 1944.19
  5174.7 1944.74  5191.1 1945.92  5201.3 1945.51  5221.6 1945.66  5272.4 1946.88
  5292.8 1947.85  5363.9 1948.28  5420.3 1949.50  5477.6 1950.19  5627.8 1950.47
#Mann=3,-1,0
  4348.4    0.05       0  5055.9    0.03       0  5059.9    0.05       0
Bank Sta=5055.9,5059.9
Exp/Cntr=0.3,0.1

Type RM Length L Ch R = 1,1706,284,284,284
BEGIN DESCRIPTION:
Mapping XS 43a758fa
END DESCRIPTION:
XS GIS Cut Line= 4
      1577705.77      6770033.80      1577674.52      6770520.79
      1577742.23      6771005.17      1577973.96      6771187.43
#Sta/Elev= 30
  4297.9 1949.81  4422.4 1949.46  4642.8 1947.16  4699.1 1945.93  4785.9 1944.65
  4803.3 1944.00  4833.6 1943.77  4873.9 1942.60  4914.3 1941.95  4954.7 1940.69
  4964.8 1940.52  4969.9 1941.04  4985.0 1941.20  5023.4 1940.22  5023.7 1939.72
  5027.2 1939.72  5027.4 1940.22  5096.1 1941.52  5106.2 1942.15  5117.9 1942.09
  5126.4 1942.62  5136.5 1942.80  5176.9 1943.17  5247.5 1944.65  5300.7 1944.82
  5371.2 1946.15  5400.1 1946.14  5435.4 1946.79  5485.1 1948.20  5569.8 1949.67
#Mann=3,-1,0
  4297.9    0.05       0  5023.4    0.03       0  5027.4    0.05       0
Bank Sta=5023.4,5027.4
Exp/Cntr=0.3,0.1

Type RM Length L Ch R = 1,1422,182,182,182
BEGIN DESCRIPTION:
Mapping XS 10561e18
END DESCRIPTION:
XS GIS Cut Line= 4
      1577474.00      6769986.98      1577432.33      6770447.87
      1577411.50      6770984.33      1577730.90      6771316.71
#Sta/Elev= 30
  4246.2 1946.11  4623.8 1944.73  4689.0 1943.79  4739.1 1943.68  4939.3 1939.71
  4949.3 1940.16  5007.3 1939.38  5007.6 1938.88  5011.1 1938.88  5011.3 1939.38
  5019.3 1939.54  5025.6 1940.21  5030.6 1940.00  5049.4 1940.67  5089.4 1940.95
  5099.4 1941.97  5109.4 1941.38  5119.4 1941.37  5149.4 1942.05  5189.5 1942.07
  5245.2 1942.98  5470.2 1943.81  5526.8 1944.94  5533.8 1944.62  5583.4 1944.63
  5604.5 1945.35  5618.7 1945.34  5625.6 1945.79  5703.6 1946.32  5706.8 1946.64
#Mann=3,-1,0
  4246.2    0.05       0  5007.3    0.03       0  5011.3    0.05       0
Bank Sta=5007.3,5011.3
Exp/Cntr=0.3,0.1

Type RM Length L Ch R = 1,1240,223,223,223
BEGIN DESCRIPTION:
Mapping XS a0d5a835
END DESCRIPTION:
XS GIS Cut Line= 4
      1577390.65      6769973.96      1577226.60      6770416.62
      1577255.25      6771023.39      1577681.14      6771360.99
#Sta/Elev= 30
  4192.7 1945.15  4261.0 1944.94  4481.0 1942.83  4644.9 1942.65  4846.4 1940.55
  4936.5 1939.11  4976.5 1939.39  4986.5 1939.01  4994.5 1937.89  4994.8 1937.39
  4998.3 1937.39  4998.5 1937.89  5026.6 1939.44  5046.6 1939.30  5086.6 1939.94
  5106.7 1939.52  5146.7 1939.96  5161.3 1940.55  5196.8 1940.19  5226.8 1940.89
  5297.4 1941.01  5318.2 1941.66  5324.6 1941.28  5496.1 1943.08  5645.1 1943.20
  5717.2 1944.61  5781.3 1944.40  5802.2 1945.14  5808.5 1944.87  5815.7 1945.43
#Mann=3,-1,0
  4192.7    0.05       0  4994.5    0.03       0  4998.5    0.05       0
Bank Sta=4994.5,4998.5
Exp/Cntr=0.3,0.1

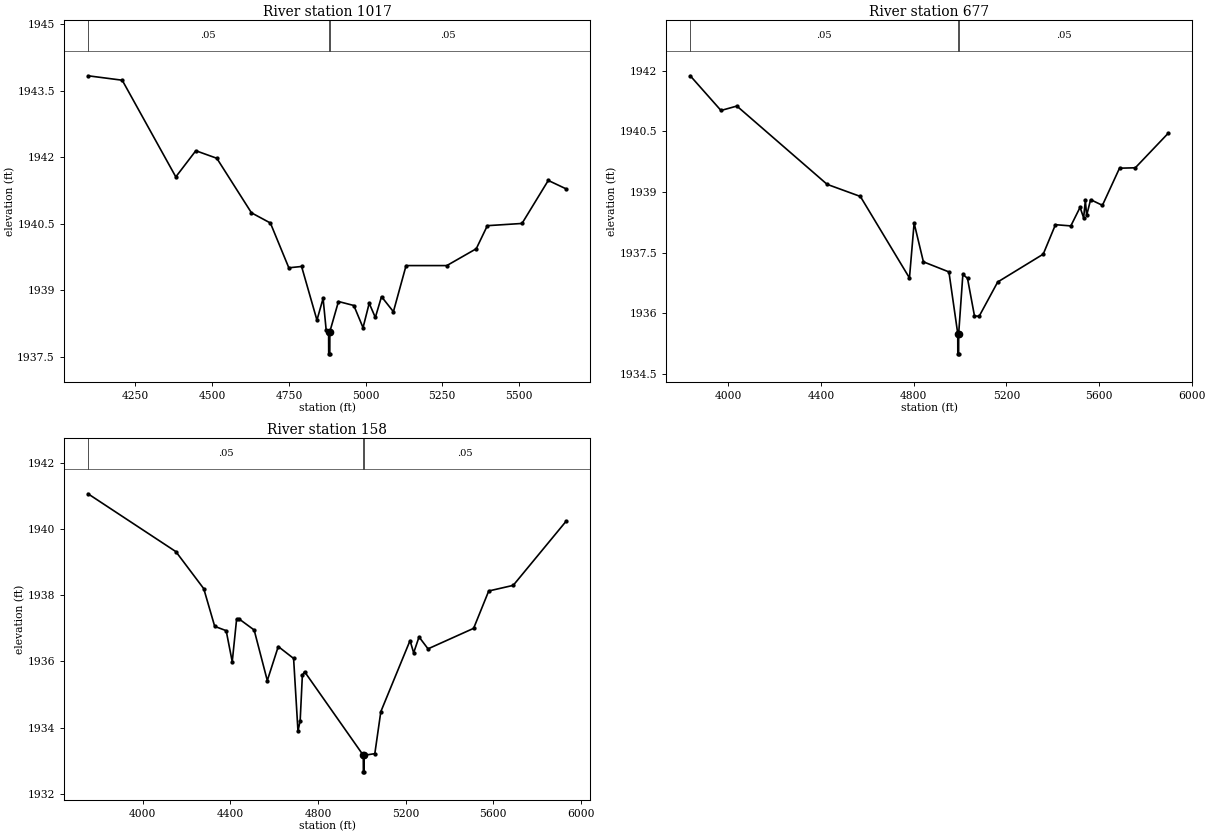
Type RM Length L Ch R = 1,1017,340,340,340
BEGIN DESCRIPTION:
Mapping XS cf1ede34
END DESCRIPTION:
XS GIS Cut Line= 4
      1577200.57      6769989.52      1577049.52      6770627.56
      1577080.77      6771151.00      1577367.19      6771398.36
#Sta/Elev= 30
  4095.2 1943.84  4206.7 1943.74  4381.4 1941.56  4446.6 1942.15  4515.0 1941.98
  4628.0 1940.75  4689.7 1940.52  4749.8 1939.51  4791.4 1939.54  4841.5 1938.33
  4861.5 1938.82  4871.5 1938.11  4879.5 1938.07  4879.8 1937.57  4883.3 1937.57
  4883.5 1938.07  4911.6 1938.75  4961.7 1938.66  4991.7 1938.16  5011.8 1938.71
  5031.8 1938.39  5051.9 1938.86  5090.7 1938.52  5132.0 1939.56  5264.8 1939.56
  5360.8 1939.94  5396.9 1940.46  5509.9 1940.51  5595.5 1941.48  5653.7 1941.29
#Mann=3,-1,0
  4095.2    0.05       0  4879.5    0.03       0  4883.5    0.05       0
Bank Sta=4879.5,4883.5
Exp/Cntr=0.3,0.1

Type RM Length L Ch R = 1,677,519,519,519
BEGIN DESCRIPTION:
Mapping XS 09c552bd
END DESCRIPTION:
XS GIS Cut Line= 4
      1576591.20      6769791.67      1576768.27      6770575.48
      1576726.60      6771171.83      1577325.57      6771455.69
#Sta/Elev= 30
  3835.2 1941.88  3967.9 1941.02  4036.5 1941.13  4426.1 1939.19  4569.6 1938.89
  4781.6 1936.87  4801.7 1938.23  4841.8 1937.27  4952.0 1937.02  4990.1 1935.49
  4990.4 1934.99  4993.9 1934.99  4994.1 1935.49  5012.2 1936.96  5032.2 1936.86
  5062.3 1935.93  5082.4 1935.92  5162.6 1936.77  5359.1 1937.46  5411.9 1938.19
  5478.3 1938.16  5518.2 1938.62  5533.6 1938.36  5541.0 1938.79  5546.5 1938.42
  5563.7 1938.81  5614.7 1938.67  5688.5 1939.59  5756.7 1939.60  5899.4 1940.46
#Mann=3,-1,0
  3835.2    0.05       0  4990.1    0.03       0  4994.1    0.05       0
Bank Sta=4990.1,4994.1
Exp/Cntr=0.3,0.1

Type RM Length L Ch R = 1,158,0,0,0
BEGIN DESCRIPTION:
Elm 01 64 1.0
END DESCRIPTION:
XS GIS Cut Line= 6
      1576487.02      6770059.88      1576487.02      6770460.89
      1576484.42      6770687.46      1576481.81      6771361.94
      1577065.15      6771494.75      1577346.40      6771494.75
#Sta/Elev= 30
  3750.7 1941.07  4151.7 1939.32  4278.8 1938.20  4328.8 1937.06  4381.1 1936.93
  4408.8 1935.99  4428.8 1937.28  4438.8 1937.29  4508.8 1936.95  4568.8 1935.42
  4618.8 1936.45  4688.8 1936.09  4708.8 1933.89  4718.8 1934.21  4728.8 1935.58
  4738.8 1935.69  5006.8 1933.16  5007.1 1932.66  5010.6 1932.66  5010.8 1933.16
  5059.4 1933.21  5086.8 1934.48  5220.1 1936.63  5236.6 1936.26  5261.2 1936.74
  5302.2 1936.38  5510.2 1937.00  5579.1 1938.13  5690.9 1938.30  5932.3 1940.24
#Mann=3,-1,0
  3750.7    0.05       0  5006.8    0.05       0  5010.8    0.05       0
Bank Sta=5006.8,5010.8
Exp/Cntr=0.3,0.1

Chan Stop Cuts=-1