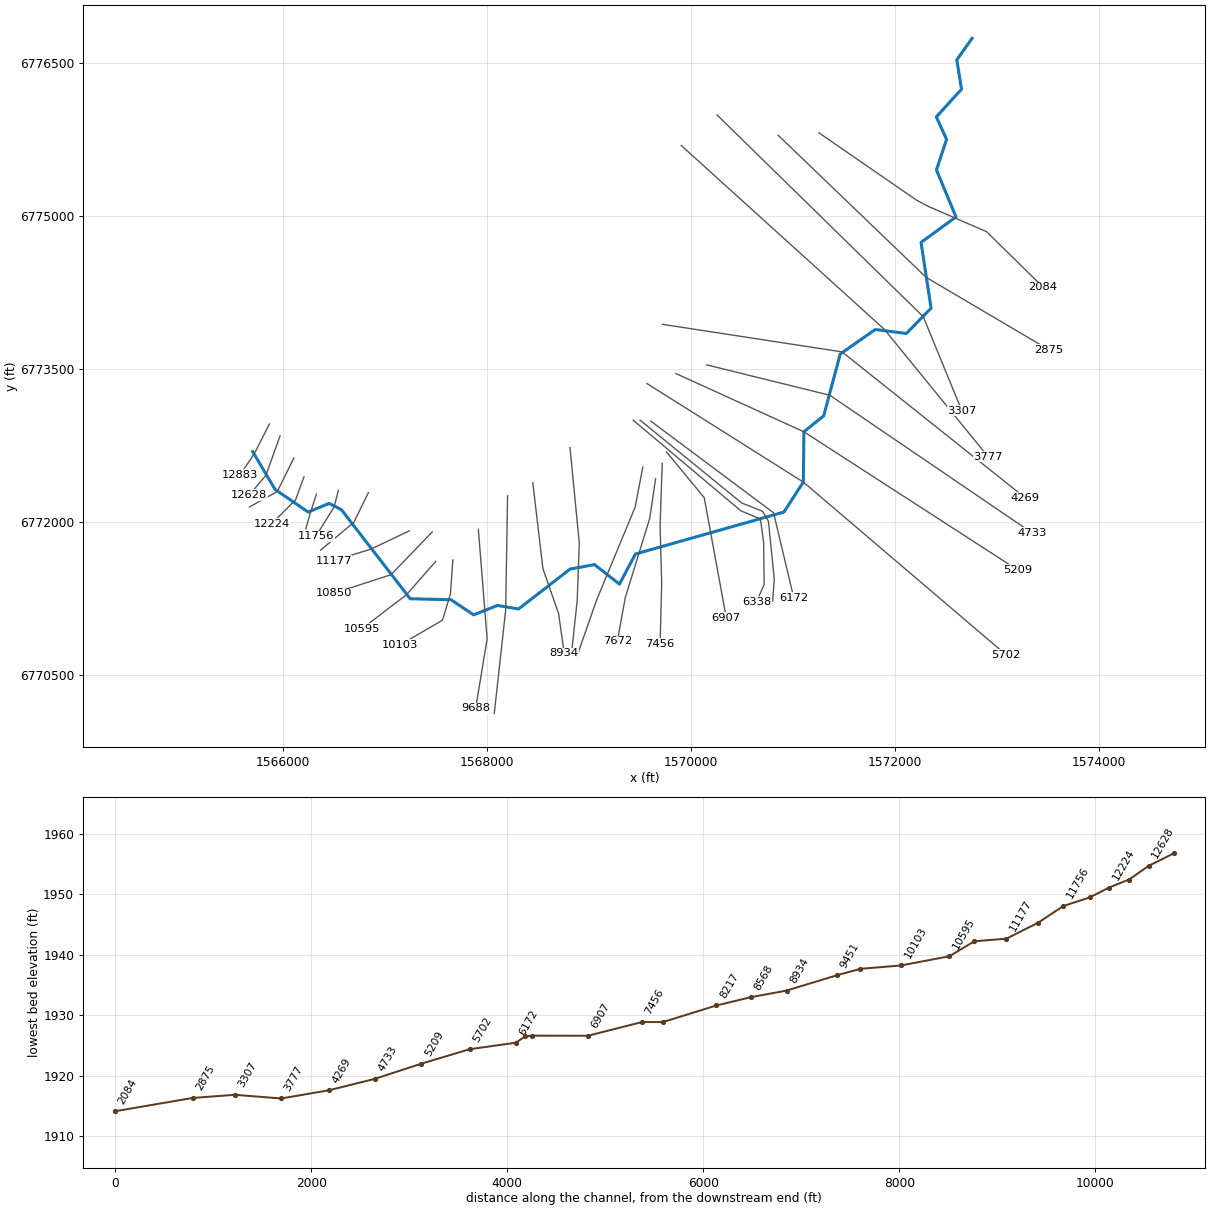
--- Elm 01 65.prj (project) ---

Proj Title=Elm 01 65 Base Level Engineering
Current Plan=p01
Default Exp/Contr=0.3,0.1
English Units
Geom File=g01
Flow File=f01
Plan File=p01
Y Axis Title=Elevation
X Axis Title(PF)=Main Channel Distance
X Axis Title(XS)=Station
BEGIN DESCRIPTION:
Elm 01 65
END DESCRIPTION:
DSS Export Rating Curves= 0
DSS Export Rating Curve Sorted= 0
DSS Export Volume Flow Curves= 0
DXF OffsetX= 0
DXF OffsetY= 0
DXF ScaleX= 1
DXF ScaleY= 10

--- Elm 01 65.p01 (plan) ---

Plan Title=Multiple Run
Short Identifier=Multiple
Geom File=g01
Flow File=f01
Subcritical Flow
K Sum by GR= 0
Std Step Tol= 0.01
Critical Tol= 0.01
Num of Std Step Trials= 20
Max Error Tol= 0.3
Flow Tol Ratio= 0.001
Split Flow NTrial= 30
Split Flow Tol= 0.02
Split Flow Ratio= 0.02
Log Output Level= 0
Friction Slope Method= 1
Unsteady Friction Slope Method= 2
Unsteady Bridges Friction Slope Method= 1
Parabolic Critical Depth
Global Vel Dist=  1 , 1 , 1
Global Log Level= 0
CheckData=True
Encroach Param= -1, 0, 0, 0
BEGIN DESCRIPTION:
Multiple Run
END DESCRIPTION:

--- Elm 01 65.f01 (steady flow) ---

Flow Title=Multiple
Program Version=4.10
Number of Profiles= 7
Profile Names=10-year,25-year,50-year,1pct_min,100-year,1pct_plu,500-year
River Rch & RM=Elm 01 65,Reach-1         ,12883
     155     210     254     191     305     420     448
River Rch & RM=Elm 01 65,Reach-1         ,9688
     210     288     350     265     424     583     629
River Rch & RM=Elm 01 65,Reach-1         ,9451
     210     288     350     265     424     583     629
River Rch & RM=Elm 01 65,Reach-1         ,8934
     282     390     479     364     583     803     877
River Rch & RM=Elm 01 65,Reach-1         ,5702
     375     526     652     500     801    1100    1230
River Rch & RM=Elm 01 65,Reach-1         ,3307
     512     727     909     702    1120    1550    1750
River Rch & RM=Elm 01 65,Reach-1         ,2084
     512     727     909     702    1120    1550    1750
River Rch & RM=Elm 01 65,Reach-1         ,661
     512     727     909     702    1120    1550    1750
Boundary for River Rch & Prof#=Elm 01 65,Reach-1         , 1
Up Type= 0
Dn Type= 3
Dn Slope=0.001
Boundary for River Rch & Prof#=Elm 01 65,Reach-1         , 2
Up Type= 0
Dn Type= 3
Dn Slope=0.001
Boundary for River Rch & Prof#=Elm 01 65,Reach-1         , 3
Up Type= 0
Dn Type= 3
Dn Slope=0.001
Boundary for River Rch & Prof#=Elm 01 65,Reach-1         , 4
Up Type= 0
Dn Type= 3
Dn Slope=0.001
Boundary for River Rch & Prof#=Elm 01 65,Reach-1         , 5
Up Type= 0
Dn Type= 3
Dn Slope=0.001
Boundary for River Rch & Prof#=Elm 01 65,Reach-1         , 6
Up Type= 0
Dn Type= 3
Dn Slope=0.001
Boundary for River Rch & Prof#=Elm 01 65,Reach-1         , 7
Up Type= 0
Dn Type= 3
Dn Slope=0.001
DSS Import GetInterval= 0
DSS Import GetPeak= 0
DSS Import FillOption= 0

--- Elm 01 65.g01 (geometry) ---

Geom Title=Existing Conditions

River Reach=Elm 01 65,Reach-1
Reach XY= 30
      1565705.00      6772688.00      1565924.63      6772317.52
      1566248.94      6772095.48      1566455.00      6772180.50
      1566575.09      6772118.23      1567248.67      6771246.00
      1567648.96      6771236.37      1567870.27      6771088.37
      1568104.99      6771180.52      1568311.22      6771145.75
      1568815.50      6771536.78      1569055.30      6771580.74
      1569299.15      6771389.49      1569456.25      6771684.55
      1570911.52      6772095.68      1571101.46      6772389.46
      1571107.05      6772882.16      1571301.48      6773039.28
      1571463.02      6773644.34      1571806.47      6773884.46
      1572111.22      6773845.74      1572353.38      6774094.03
      1572255.00      6774738.00      1572597.71      6774987.91
      1572406.10      6775448.55      1572505.55      6775748.18
      1572404.68      6775968.13      1572651.47      6776239.45
      1572605.60      6776527.38      1572755.00      6776738.00

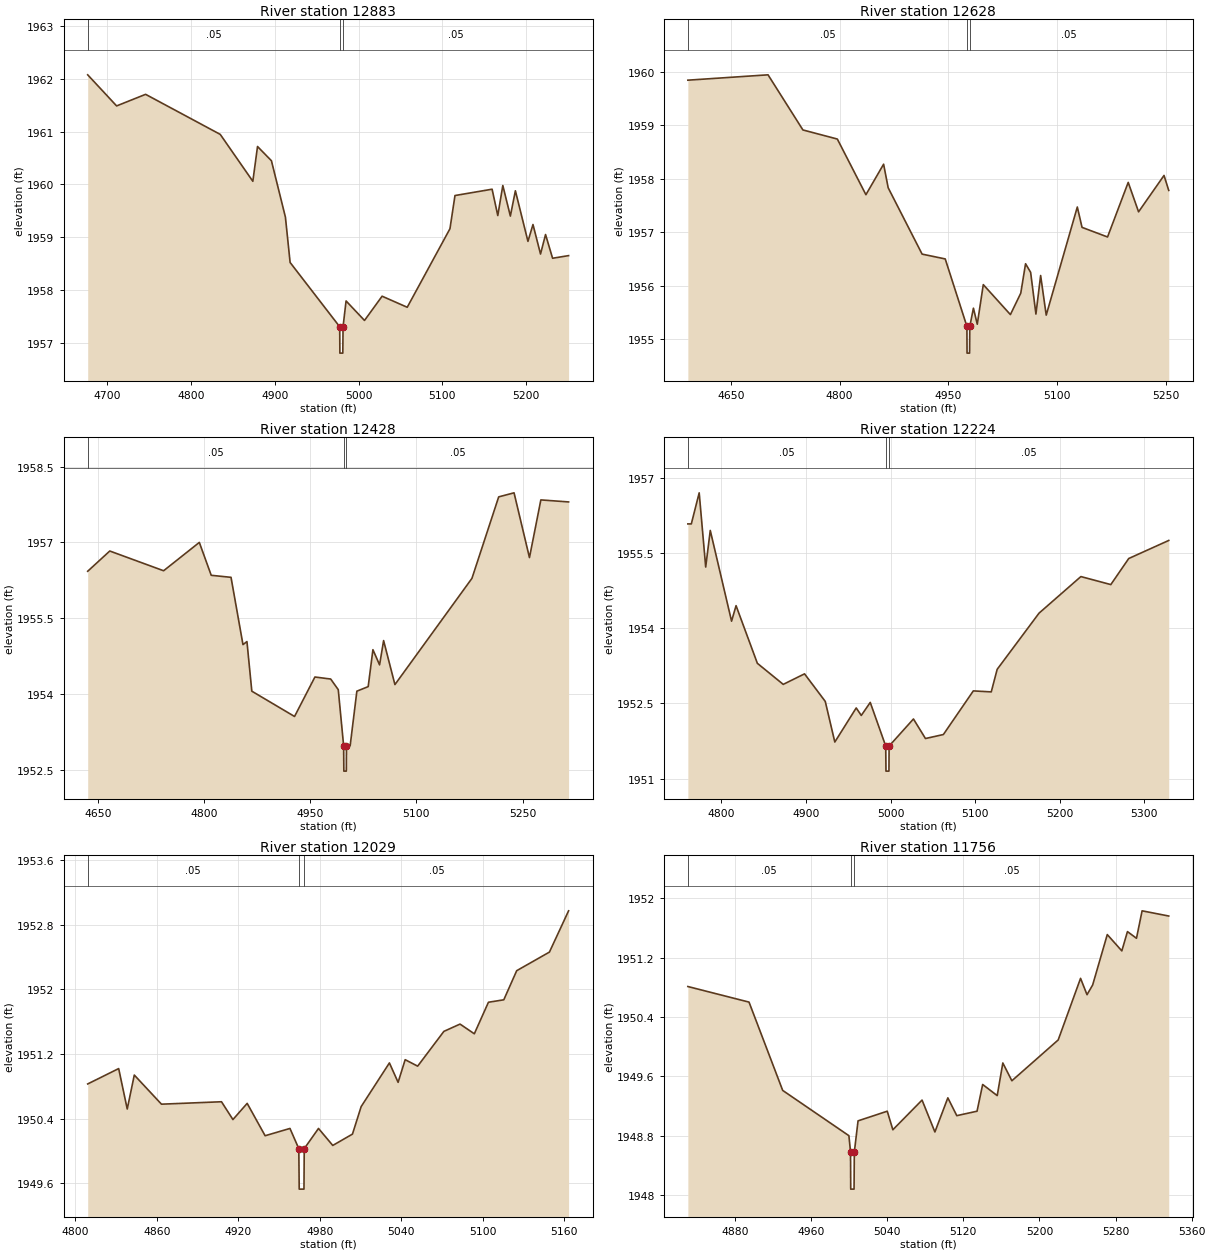
Type RM Length L Ch R = 1,12883,255,255,255
BEGIN DESCRIPTION:
Elm 01 65 12416.235
END DESCRIPTION:
XS GIS Cut Line= 3
      1565869.23      6772958.73      1565722.82      6772670.37
      1565583.34      6772462.17
#Sta/Elev= 30
  4676.6 1962.08  4711.1 1961.49  4745.7 1961.71  4834.8 1960.95  4873.7 1960.06
  4879.3 1960.72  4895.9 1960.45  4912.6 1959.38  4918.2 1958.52  4977.4 1957.30
  4977.6 1956.80  4981.1 1956.80  4981.4 1957.30  4985.0 1957.79  5007.0 1957.42
  5028.0 1957.88  5058.0 1957.67  5109.0 1959.16  5115.0 1959.79  5159.3 1959.91
  5166.1 1959.41  5172.1 1959.98  5181.1 1959.40  5187.1 1959.88  5202.1 1958.92
  5208.1 1959.24  5217.1 1958.68  5223.1 1959.05  5231.5 1958.60  5250.6 1958.65
#Mann=3,-1,0
  4676.6    0.05       0  4977.4    0.05       0  4981.4    0.05       0
Bank Sta=4977.4,4981.4
Exp/Cntr=0.3,0.1

Type RM Length L Ch R = 1,12628,200,200,200
BEGIN DESCRIPTION:
Elm 01 65 12628.34
END DESCRIPTION:
XS GIS Cut Line= 3
      1565973.70      6772842.11      1565834.39      6772454.13
      1565671.75      6772262.86
#Sta/Elev= 30
  4590.8 1959.84  4701.4 1959.94  4749.5 1958.91  4797.0 1958.74  4836.4 1957.70
  4860.8 1958.27  4867.1 1957.83  4913.9 1956.59  4945.8 1956.50  4975.7 1955.24
  4975.9 1954.74  4979.4 1954.74  4979.7 1955.24  4984.7 1955.58  4990.0 1955.28
  4998.3 1956.02  5035.7 1955.46  5050.0 1955.86  5056.6 1956.41  5063.6 1956.25
  5070.9 1955.47  5077.4 1956.19  5085.1 1955.45  5128.0 1957.47  5134.5 1957.09
  5169.7 1956.91  5198.2 1957.93  5212.5 1957.38  5247.6 1958.06  5254.1 1957.78
#Mann=3,-1,0
  4590.8    0.05       0  4975.7    0.05       0  4979.7    0.05       0
Bank Sta=4975.7,4979.7
Exp/Cntr=0.3,0.1

Type RM Length L Ch R = 1,12428,204,204,204
BEGIN DESCRIPTION:
Elm 01 65 12427.61
END DESCRIPTION:
XS GIS Cut Line= 3
      1566109.11      6772625.97      1565946.37      6772296.58
      1565672.92      6772145.53
#Sta/Elev= 30
  4635.3 1956.43  4666.5 1956.83  4742.6 1956.44  4793.1 1957.00  4809.9 1956.35
  4837.9 1956.31  4854.8 1954.98  4860.4 1955.04  4867.3 1954.06  4927.7 1953.56
  4956.5 1954.34  4978.8 1954.30  4989.5 1954.09  4997.1 1952.98  4997.4 1952.48
  5000.9 1952.48  5001.1 1952.98  5006.3 1952.98  5015.8 1954.06  5031.8 1954.15
  5038.5 1954.88  5047.9 1954.58  5053.6 1955.06  5069.6 1954.19  5178.5 1956.29
  5216.3 1957.90  5238.0 1957.98  5259.8 1956.70  5275.9 1957.84  5315.1 1957.80
#Mann=3,-1,0
  4635.3    0.05       0  4997.1    0.05       0  5001.1    0.05       0
Bank Sta=4997.1,5001.1
Exp/Cntr=0.3,0.1

Type RM Length L Ch R = 1,12224,195,195,195
BEGIN DESCRIPTION:
Elm 01 65 12224.32
END DESCRIPTION:
XS GIS Cut Line= 3
      1566208.07      6772440.62      1566125.60      6772214.90
      1565892.96      6771983.13
#Sta/Elev= 30
  4760.3 1956.08  4764.4 1956.08  4773.7 1956.70  4781.4 1955.22  4786.8 1955.95
  4812.0 1954.14  4817.3 1954.45  4842.5 1953.30  4873.1 1952.88  4898.3 1953.09
  4922.8 1952.54  4934.1 1951.73  4959.4 1952.41  4965.4 1952.26  4976.0 1952.52
  4994.3 1951.65  4994.6 1951.15  4998.1 1951.15  4998.3 1951.65  5027.1 1952.19
  5041.3 1951.80  5062.5 1951.88  5097.9 1952.75  5119.1 1952.73  5126.1 1953.18
  5175.6 1954.30  5225.1 1955.03  5260.5 1954.87  5281.7 1955.39  5329.0 1955.75
#Mann=3,-1,0
  4760.3    0.05       0  4994.3    0.05       0  4998.3    0.05       0
Bank Sta=4994.3,4998.3
Exp/Cntr=0.3,0.1

Type RM Length L Ch R = 1,12029,273,273,273
BEGIN DESCRIPTION:
Elm 01 65 12029.28
END DESCRIPTION:
XS GIS Cut Line= 3
      1566329.23      6772269.71      1566270.90      6772088.47
      1566225.59      6771931.27
#Sta/Elev= 30
  4809.1 1950.83  4831.9 1951.02  4838.2 1950.52  4843.4 1950.94  4863.4 1950.58
  4907.6 1950.61  4916.0 1950.39  4926.5 1950.59  4939.7 1950.19  4958.0 1950.28
  4964.5 1950.03  4964.8 1949.53  4968.3 1949.53  4968.5 1950.03  4979.0 1950.28
  4989.5 1950.07  5004.0 1950.21  5010.4 1950.55  5031.2 1951.09  5037.6 1950.85
  5042.8 1951.13  5052.0 1951.05  5071.3 1951.48  5083.2 1951.57  5093.7 1951.45
  5104.1 1951.84  5115.4 1951.87  5124.9 1952.23  5149.0 1952.46  5163.1 1952.97
#Mann=3,-1,0
  4809.1    0.05       0  4964.5    0.05       0  4968.5    0.05       0
Bank Sta=4964.5,4968.5
Exp/Cntr=0.3,0.1

Type RM Length L Ch R = 1,11756,252,252,252
BEGIN DESCRIPTION:
Elm 01 65 11756.19
END DESCRIPTION:
XS GIS Cut Line= 3
      1566545.20      6772308.62      1566502.84      6772144.72
      1566325.08      6771859.34
#Sta/Elev= 30
  4830.4 1950.81  4894.7 1950.60  4930.1 1949.41  4999.7 1948.80  5001.4 1948.58
  5001.6 1948.08  5005.1 1948.08  5005.4 1948.58  5009.3 1949.00  5040.0 1949.13
  5045.9 1948.88  5076.6 1949.28  5090.1 1948.85  5103.7 1949.31  5113.1 1949.07
  5134.4 1949.13  5140.3 1949.49  5155.6 1949.34  5161.5 1949.78  5171.0 1949.54
  5219.7 1950.09  5243.2 1950.92  5250.0 1950.70  5255.9 1950.83  5271.3 1951.51
  5286.6 1951.29  5292.5 1951.55  5302.0 1951.46  5307.9 1951.83  5335.9 1951.76
#Mann=3,-1,0
  4830.4    0.05       0  5001.4    0.05       0  5005.4    0.05       0
Bank Sta=5001.4,5005.4
Exp/Cntr=0.3,0.1

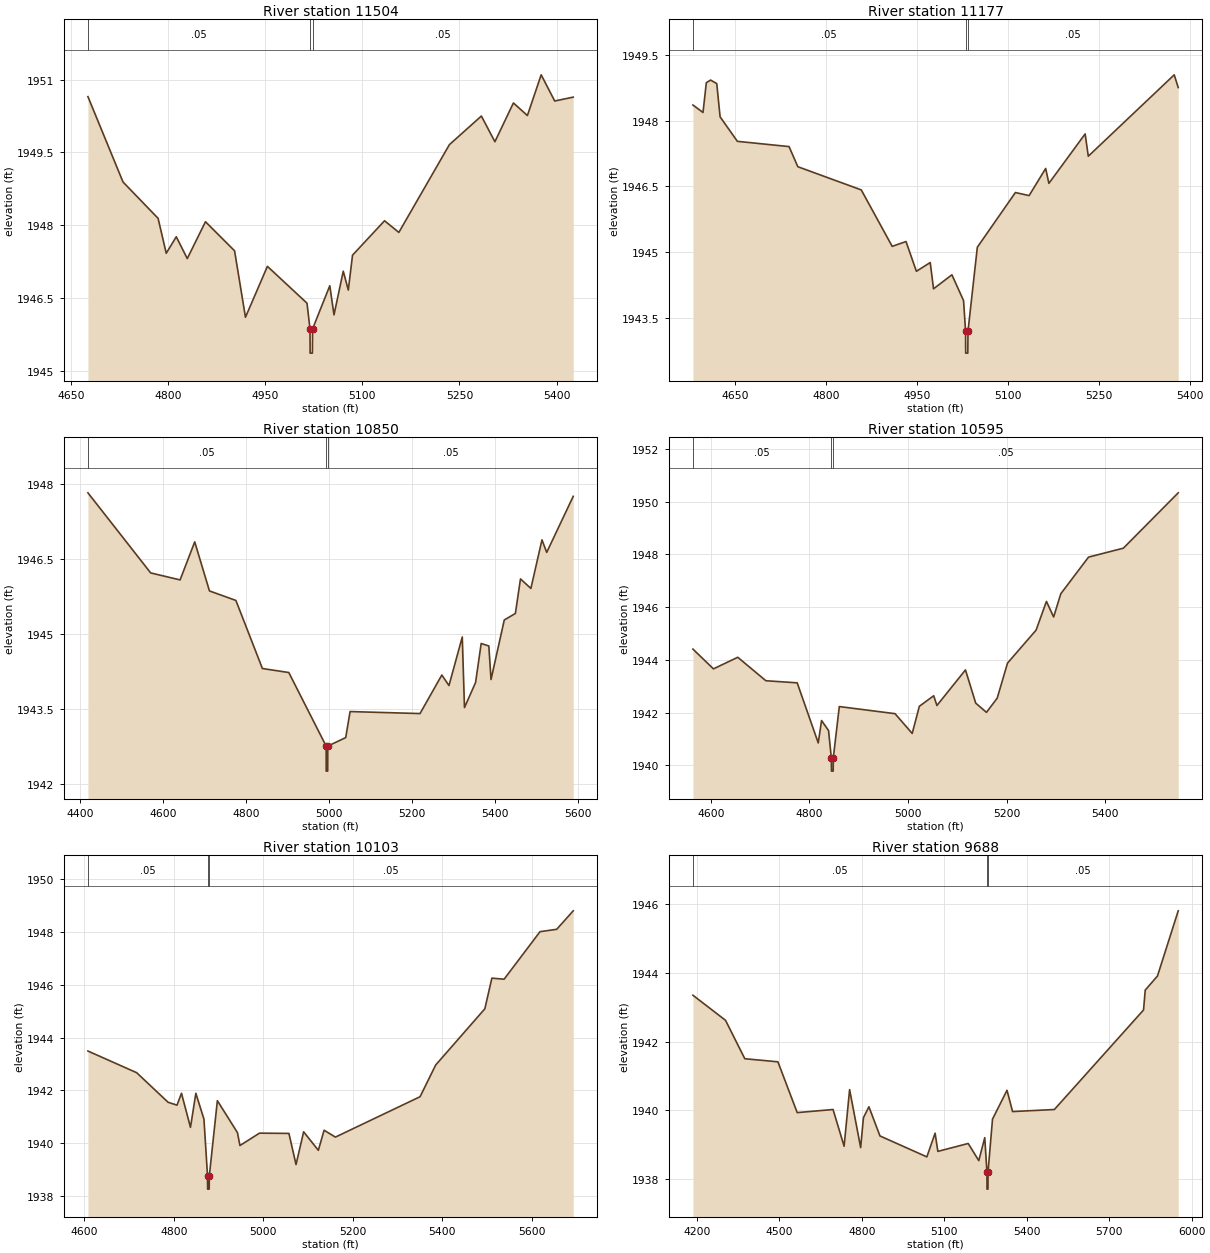
Type RM Length L Ch R = 1,11504,327,327,327
BEGIN DESCRIPTION:
Elm 01 65 11504.44
END DESCRIPTION:
XS GIS Cut Line= 3
      1566839.37      6772286.75      1566697.02      6771995.11
      1566370.67      6771722.43
#Sta/Elev= 30
  4676.0 1950.65  4730.2 1948.89  4784.4 1948.14  4797.0 1947.42  4812.5 1947.76
  4829.5 1947.31  4857.6 1948.07  4902.6 1947.47  4919.4 1946.10  4953.3 1947.15
  5014.5 1946.39  5019.1 1945.86  5019.3 1945.36  5022.8 1945.36  5023.1 1945.86
  5049.7 1946.75  5056.2 1946.15  5070.5 1947.05  5078.3 1946.66  5084.8 1947.38
  5134.3 1948.09  5156.4 1947.85  5234.5 1949.66  5283.9 1950.25  5304.8 1949.72
  5333.4 1950.52  5355.0 1950.26  5376.3 1951.10  5397.2 1950.56  5425.8 1950.64
#Mann=3,-1,0
  4676.0    0.05       0  5019.1    0.05       0  5023.1    0.05       0
Bank Sta=5019.1,5023.1
Exp/Cntr=0.3,0.1

Type RM Length L Ch R = 1,11177,327,327,327
BEGIN DESCRIPTION:
Elm 01 65 11176.93
END DESCRIPTION:
XS GIS Cut Line= 3
      1567241.26      6771911.86      1566862.79      6771732.18
      1566498.67      6771618.87
#Sta/Elev= 30
  4581.0 1948.36  4597.6 1948.19  4603.1 1948.87  4610.1 1948.93  4620.3 1948.85
  4625.8 1948.09  4654.3 1947.53  4739.5 1947.41  4754.0 1946.95  4858.6 1946.42
  4909.6 1945.13  4932.4 1945.24  4949.5 1944.56  4972.3 1944.76  4977.8 1944.16
  5008.1 1944.48  5027.3 1943.89  5030.6 1943.19  5030.8 1942.69  5034.3 1942.69
  5034.6 1943.19  5050.0 1945.11  5112.8 1946.36  5135.4 1946.29  5162.7 1946.91
  5168.0 1946.57  5227.8 1947.70  5233.0 1947.19  5374.7 1949.05  5381.3 1948.76
#Mann=3,-1,0
  4581.0    0.05       0  5030.6    0.05       0  5034.6    0.05       0
Bank Sta=5030.6,5034.6
Exp/Cntr=0.3,0.1

Type RM Length L Ch R = 1,10850,255,255,255
BEGIN DESCRIPTION:
Elm 01 65 10850.2
END DESCRIPTION:
XS GIS Cut Line= 3
      1567465.20      6771901.34      1567061.58      6771482.09
      1566504.29      6771301.10
#Sta/Elev= 30
  4419.6 1947.82  4570.6 1946.22  4641.4 1946.08  4676.6 1946.84  4712.1 1945.86
  4775.7 1945.67  4839.5 1944.31  4903.0 1944.23  4992.9 1942.76  4993.1 1942.26
  4996.6 1942.26  4996.9 1942.76  5040.0 1942.93  5050.5 1943.45  5218.8 1943.41
  5271.3 1944.18  5288.5 1943.97  5320.5 1944.94  5325.8 1943.53  5352.5 1944.03
  5366.0 1944.81  5384.4 1944.76  5389.7 1944.09  5421.6 1945.28  5448.3 1945.41
  5460.6 1946.10  5485.6 1945.91  5512.3 1946.88  5523.7 1946.63  5587.5 1947.75
#Mann=3,-1,0
  4419.6    0.05       0  4992.9    0.05       0  4996.9    0.05       0
Bank Sta=4992.9,4996.9
Exp/Cntr=0.3,0.1

Type RM Length L Ch R = 1,10595,492,492,492
BEGIN DESCRIPTION:
Elm 01 65 10594.95
END DESCRIPTION:
XS GIS Cut Line= 3
      1567499.11      6771612.33      1567211.32      6771284.17
      1566775.65      6770952.54
#Sta/Elev= 30
  4563.9 1944.41  4605.5 1943.66  4654.8 1944.10  4711.8 1943.21  4775.3 1943.13
  4818.0 1940.85  4824.7 1941.70  4838.9 1941.32  4844.5 1940.28  4844.8 1939.78
  4848.3 1939.78  4848.5 1940.28  4860.7 1942.23  4973.7 1941.96  5008.5 1941.21
  5023.0 1942.24  5052.1 1942.64  5058.6 1942.27  5116.5 1943.62  5137.3 1942.36
  5159.1 1942.01  5180.9 1942.55  5201.8 1943.88  5259.7 1945.13  5280.7 1946.22
  5295.3 1945.63  5309.8 1946.51  5366.0 1947.90  5436.7 1948.24  5547.9 1950.34
#Mann=3,-1,0
  4563.9    0.05       0  4844.5    0.03       0  4848.5    0.05       0
Bank Sta=4844.5,4848.5
Exp/Cntr=0.3,0.1

Type RM Length L Ch R = 1,10103,415,415,415
BEGIN DESCRIPTION:
Mapping XS a571e7c8
END DESCRIPTION:
XS GIS Cut Line= 4
      1567666.71      6771626.63      1567643.27      6771293.29
      1567565.15      6771035.47      1567149.26      6770793.74
#Sta/Elev= 30
  4608.3 1943.49  4717.2 1942.67  4787.4 1941.55  4807.4 1941.44  4817.4 1941.89
  4837.5 1940.60  4849.5 1941.89  4867.6 1940.91  4875.6 1938.76  4875.8 1938.26
  4879.3 1938.26  4879.6 1938.76  4897.6 1941.61  4942.5 1940.40  4948.0 1939.91
  4991.6 1940.38  5057.5 1940.37  5073.4 1939.19  5090.4 1940.43  5123.3 1939.73
  5136.1 1940.49  5161.4 1940.23  5350.6 1941.76  5385.5 1942.96  5495.4 1945.09
  5511.1 1946.25  5538.4 1946.21  5618.7 1948.01  5656.0 1948.10  5692.9 1948.80
#Mann=3,-1,0
  4608.3    0.05       0  4875.6    0.05       0  4879.6    0.05       0
Bank Sta=4875.6,4879.6
Exp/Cntr=0.3,0.1

Type RM Length L Ch R = 1,9688,237,237,237
BEGIN DESCRIPTION:
Elm 01 65 10035.81
END DESCRIPTION:
XS GIS Cut Line= 3
      1567916.71      6771926.10      1568002.65      6770853.18
      1567890.67      6770173.50
#Sta/Elev= 30
  4186.0 1943.35  4304.5 1942.62  4374.7 1941.50  4495.1 1941.41  4565.3 1939.93
  4695.7 1940.02  4735.9 1938.95  4755.9 1940.60  4796.1 1938.91  4806.1 1939.78
  4826.1 1940.10  4866.3 1939.25  5036.8 1938.64  5066.9 1939.33  5076.9 1938.80
  5187.3 1939.03  5225.8 1938.53  5247.5 1939.20  5255.4 1938.20  5255.7 1937.70
  5259.2 1937.70  5259.4 1938.20  5275.7 1939.74  5328.4 1940.58  5348.7 1939.96
  5500.7 1940.02  5825.0 1942.92  5831.2 1943.50  5875.7 1943.91  5951.2 1945.81
#Mann=3,-1,0
  4186.0    0.05       0  5255.4    0.05       0  5259.4    0.05       0
Bank Sta=5255.4,5259.4
Exp/Cntr=0.3,0.1

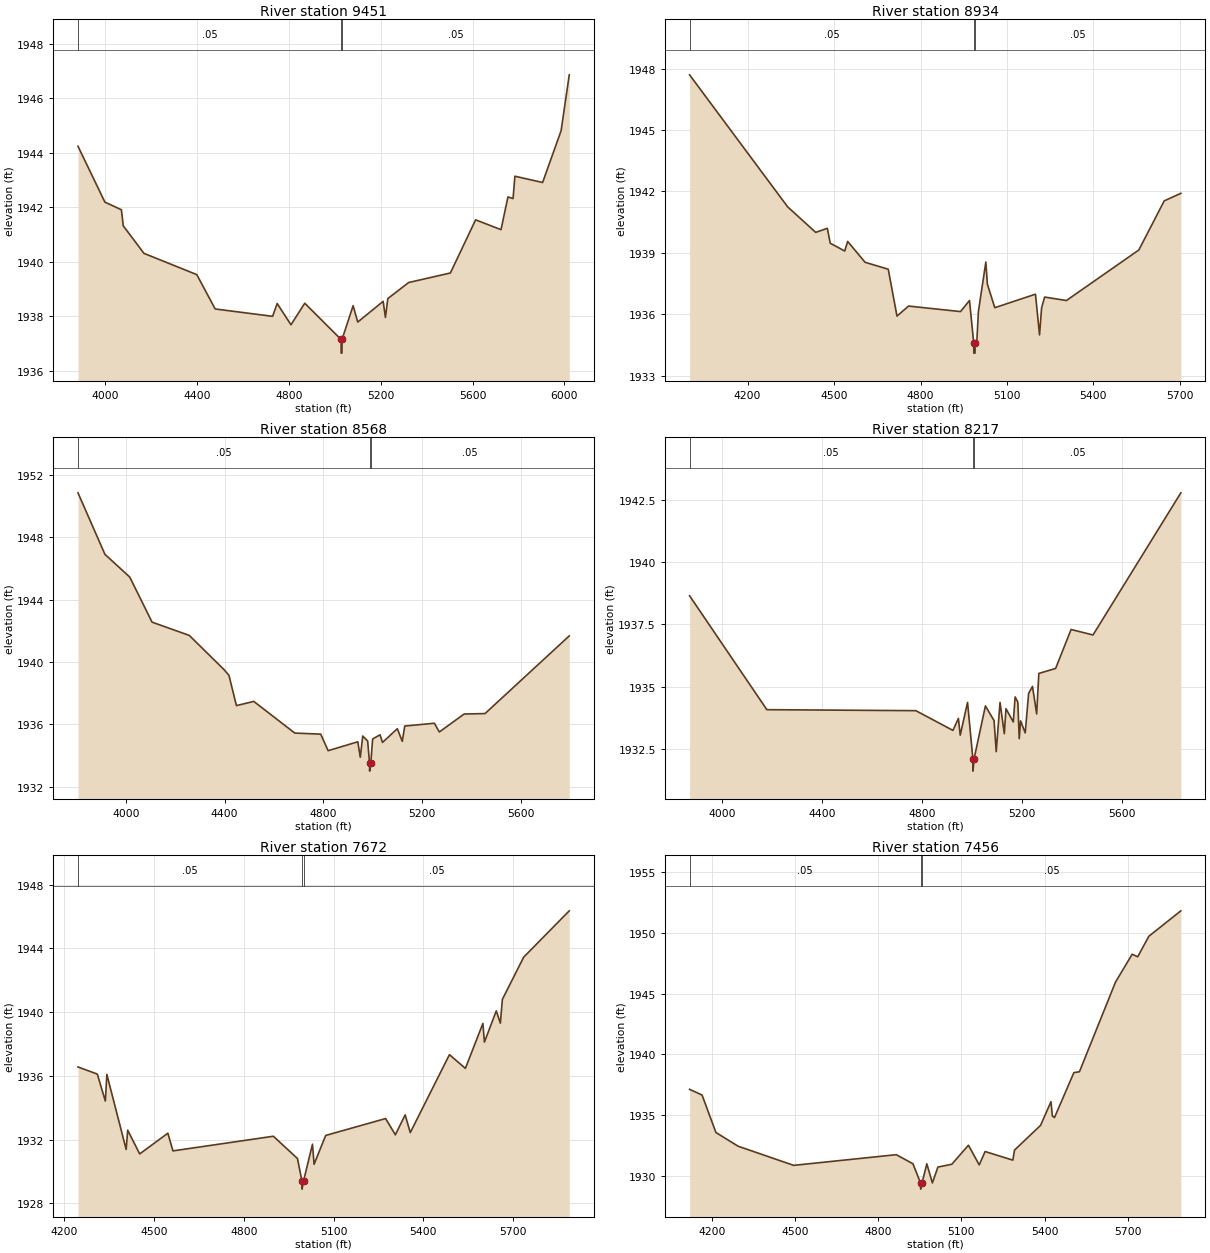
Type RM Length L Ch R = 1,9451,517,517,517
BEGIN DESCRIPTION:
Elm 01 65 10053.703
END DESCRIPTION:
XS GIS Cut Line= 3
      1568203.05      6772255.21      1568184.70      6771137.47
      1568072.87      6770122.71
#Sta/Elev= 30
  3882.1 1944.24  3999.3 1942.19  4071.1 1941.91  4079.3 1941.32  4169.4 1940.31
  4399.4 1939.53  4479.4 1938.27  4729.4 1938.00  4749.4 1938.47  4809.4 1937.69
  4869.4 1938.48  5027.6 1937.15  5027.9 1936.65  5031.4 1936.65  5031.6 1937.15
  5079.9 1938.39  5100.1 1937.79  5210.7 1938.55  5220.6 1937.96  5230.9 1938.65
  5321.6 1939.24  5503.4 1939.59  5613.2 1941.54  5723.8 1941.18  5754.0 1942.38
  5776.2 1942.32  5784.2 1943.14  5904.9 1942.91  5985.4 1944.81  6020.9 1946.86
#Mann=3,-1,0
  3882.1    0.05       0  5027.6    0.05       0  5031.6    0.05       0
Bank Sta=5027.6,5031.6
Exp/Cntr=0.3,0.1

Type RM Length L Ch R = 1,8934,366,366,366
BEGIN DESCRIPTION:
Mapping XS 4d7b2fcc
END DESCRIPTION:
XS GIS Cut Line= 4
      1568450.45      6772382.82      1568549.40      6771541.70
      1568703.05      6771101.59      1568757.73      6770713.61
#Sta/Elev= 30
  3998.6 1947.70  4338.9 1941.25  4436.4 1940.00  4476.7 1940.20  4486.8 1939.47
  4537.1 1939.09  4547.2 1939.56  4607.6 1938.54  4688.1 1938.20  4718.4 1935.91
  4758.6 1936.40  4938.9 1936.13  4970.0 1936.67  4984.7 1934.60  4985.1 1934.10
  4989.2 1934.10  4989.6 1934.60  4995.7 1934.74  5001.0 1936.14  5026.8 1938.55
  5032.1 1937.47  5057.8 1936.32  5199.0 1936.98  5213.1 1934.99  5220.2 1936.31
  5230.8 1936.84  5306.3 1936.67  5557.7 1939.14  5645.8 1941.54  5703.5 1941.91
#Mann=3,-1,0
  3998.6    0.05       0  4984.7    0.03       0  4989.6    0.05       0
Bank Sta=4984.7,4989.6
Exp/Cntr=0.3,0.1

Type RM Length L Ch R = 1,8568,351,351,351
BEGIN DESCRIPTION:
Mapping XS 7420b65c
END DESCRIPTION:
XS GIS Cut Line= 4
      1568815.03      6772726.57      1568906.18      6771789.09
      1568885.34      6771226.59      1568833.25      6770744.78
#Sta/Elev= 30
  3806.1 1950.84  3915.2 1946.90  4015.7 1945.44  4106.1 1942.55  4256.8 1941.70
  4397.4 1939.51  4417.5 1939.14  4447.7 1937.20  4518.0 1937.47  4684.0 1935.44
  4789.1 1935.37  4819.1 1934.31  4939.2 1934.88  4949.2 1933.89  4959.2 1935.25
  4979.2 1934.93  4986.8 1933.50  4987.1 1933.00  4991.8 1933.50  4999.3 1935.06
  5029.3 1935.33  5039.3 1934.84  5099.3 1935.72  5119.3 1934.91  5129.4 1935.89
  5249.4 1936.07  5269.4 1935.51  5369.8 1936.66  5454.5 1936.69  5795.5 1941.67
#Mann=3,-1,0
  3806.1    0.05       0  4986.8    0.05       0  4991.8    0.05       0
Bank Sta=4986.8,4991.8
Exp/Cntr=0.3,0.1

Type RM Length L Ch R = 1,8217,545,545,545
BEGIN DESCRIPTION:
Mapping XS 9551d362
END DESCRIPTION:
XS GIS Cut Line= 4
      1569528.58      6772536.53      1569453.05      6772143.26
      1569078.05      6771239.61      1568882.85      6770682.65
#Sta/Elev= 30
  3868.7 1938.65  4178.5 1934.09  4775.6 1934.05  4924.2 1933.26  4946.1 1933.74
  4953.5 1933.07  4982.8 1934.38  5004.1 1932.13  5004.5 1931.63  5009.1 1932.13
  5054.4 1934.24  5089.1 1933.65  5097.7 1932.41  5113.0 1934.38  5130.2 1933.13
  5136.8 1934.13  5166.1 1933.60  5173.5 1934.60  5184.3 1934.39  5190.0 1932.93
  5195.4 1933.64  5213.9 1933.16  5227.6 1934.74  5243.1 1935.02  5259.8 1933.92
  5268.5 1935.54  5335.8 1935.74  5397.8 1937.30  5485.6 1937.08  5837.7 1942.77
#Mann=3,-1,0
  3868.7    0.05       0  5004.1    0.05       0  5009.1    0.05       0
Bank Sta=5004.1,5009.1
Exp/Cntr=0.3,0.1

Type RM Length L Ch R = 1,7672,216,216,216
BEGIN DESCRIPTION:
Mapping XS 87410dcb
END DESCRIPTION:
XS GIS Cut Line= 4
      1569653.58      6772421.94      1569596.28      6772033.88
      1569356.70      6771257.84      1569278.57      6770828.14
#Sta/Elev= 30
  4246.2 1936.56  4310.8 1936.11  4337.6 1934.42  4342.7 1936.09  4407.2 1931.38
  4412.3 1932.59  4452.4 1931.10  4546.5 1932.40  4563.5 1931.29  4899.0 1932.21
  4979.5 1930.81  4994.4 1929.39  4994.8 1928.89  4999.6 1929.39  5029.6 1931.71
  5034.9 1930.45  5073.7 1932.26  5273.9 1933.32  5306.5 1932.30  5339.2 1933.55
  5356.3 1932.44  5487.1 1937.33  5540.4 1936.47  5598.9 1939.29  5604.0 1938.12
  5643.6 1940.08  5657.3 1939.31  5663.9 1940.80  5735.1 1943.45  5887.4 1946.36
#Mann=3,-1,0
  4246.2    0.05       0  4994.4    0.05       0  4999.6    0.05       0
Bank Sta=4994.4,4999.6
Exp/Cntr=0.3,0.1

Type RM Length L Ch R = 1,7456,549,549,549
BEGIN DESCRIPTION:
Mapping XS c7c8763e
END DESCRIPTION:
XS GIS Cut Line= 4
      1569718.68      6772572.94      1569697.84      6771960.97
      1569713.47      6771401.07      1569697.85      6770802.51
#Sta/Elev= 30
  4120.3 1937.11  4165.3 1936.64  4215.3 1933.55  4295.3 1932.42  4495.5 1930.84
  4865.6 1931.72  4925.7 1930.97  4953.1 1929.38  4953.5 1928.88  4958.3 1929.38
  4975.7 1930.97  4995.7 1929.39  5015.7 1930.70  5065.7 1930.93  5125.7 1932.50
  5164.6 1930.88  5185.8 1931.98  5285.8 1931.27  5291.8 1932.10  5385.8 1934.14
  5423.3 1936.09  5428.3 1934.91  5435.9 1934.78  5505.9 1938.49  5525.9 1938.56
  5655.9 1945.95  5716.0 1948.25  5736.0 1948.04  5776.0 1949.73  5891.5 1951.83
#Mann=3,-1,0
  4120.3    0.05       0  4953.1    0.03       0  4958.3    0.05       0
Bank Sta=4953.1,4958.3
Exp/Cntr=0.3,0.1

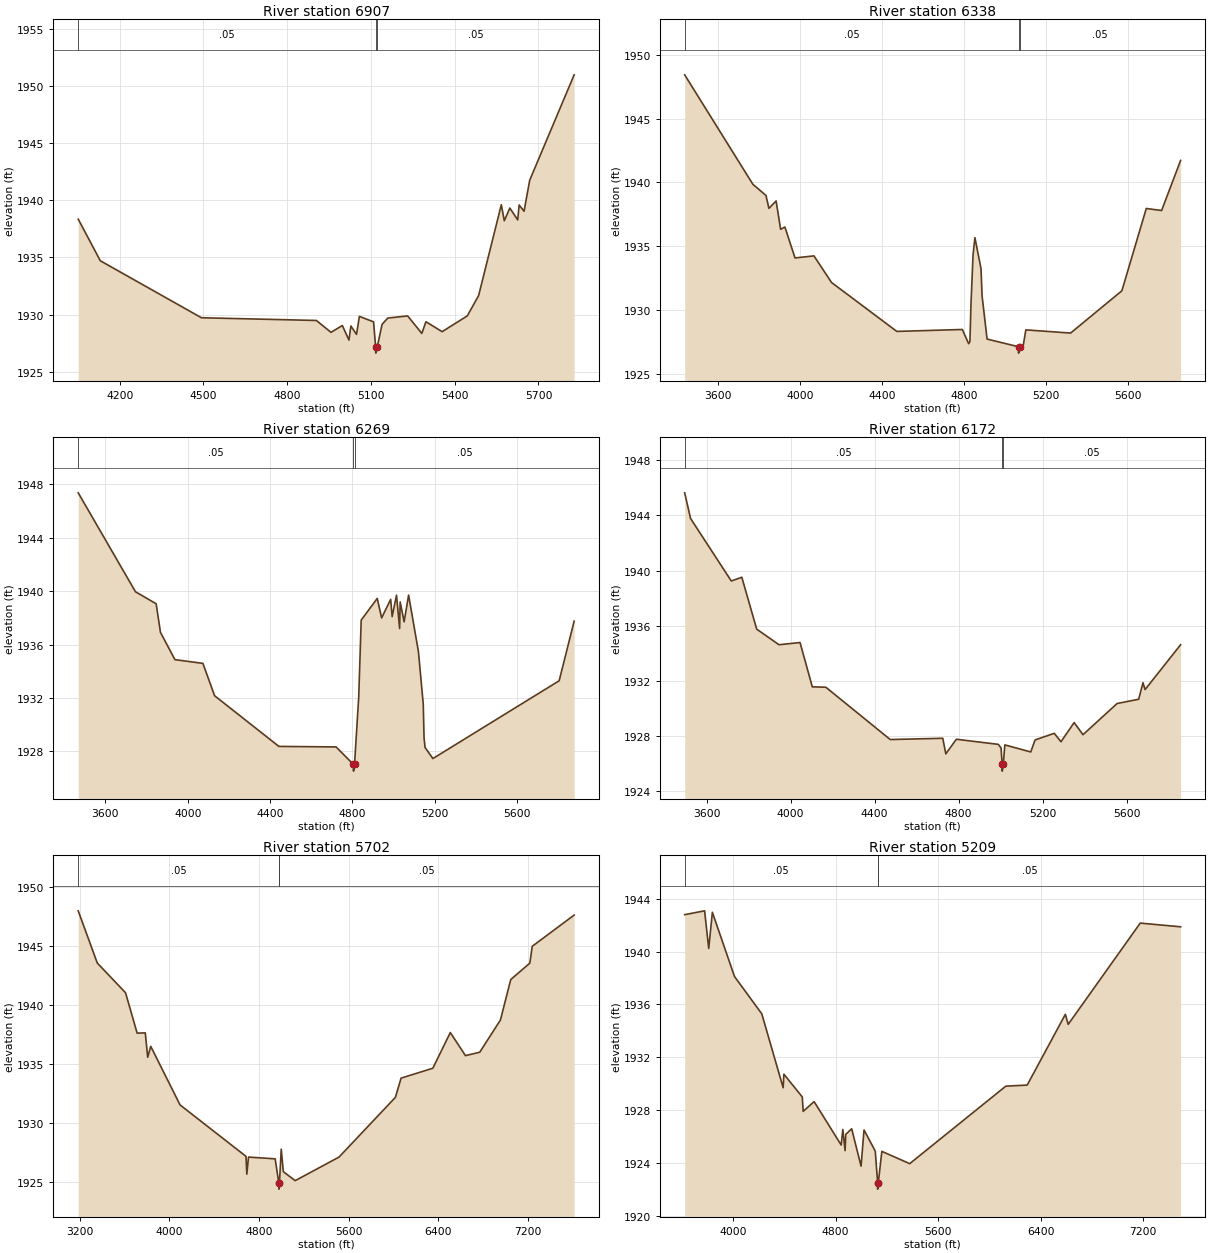
Type RM Length L Ch R = 1,6907,569,569,569
BEGIN DESCRIPTION:
Mapping XS 76528260
END DESCRIPTION:
XS GIS Cut Line= 3
      1569760.34      6772684.93      1570130.13      6772237.01
      1570345.99      6771061.51
#Sta/Elev= 30
  4051.7 1938.36  4130.9 1934.71  4493.0 1929.72  4904.8 1929.48  4956.9 1928.44
  4997.6 1929.04  5021.2 1927.76  5028.1 1929.00  5048.4 1928.26  5058.6 1929.84
  5109.4 1929.36  5116.9 1927.12  5117.4 1926.62  5122.2 1927.12  5139.9 1929.14
  5160.2 1929.69  5231.4 1929.88  5282.2 1928.35  5296.9 1929.37  5355.0 1928.50
  5444.9 1929.88  5485.6 1931.66  5566.9 1939.62  5577.6 1938.22  5597.4 1939.33
  5625.6 1938.29  5630.7 1939.60  5648.3 1939.05  5668.6 1941.77  5827.7 1951.00
#Mann=3,-1,0
  4051.7    0.05       0  5116.9    0.03       0  5122.2    0.05       0
Bank Sta=5116.9,5122.2
Exp/Cntr=0.3,0.1

Type RM Length L Ch R = 1,6338,69,69,69
BEGIN DESCRIPTION:
Mapping XS 8ac0b159
END DESCRIPTION:
XS GIS Cut Line= 6
      1569433.75      6772996.24      1570488.47      6772108.19
      1570681.18      6772027.46      1570712.43      6771800.90
      1570717.63      6771384.23      1570642.12      6771217.59
#Sta/Elev= 30
  3437.9 1948.42  3770.9 1939.85  3834.7 1938.98  3849.0 1937.97  3884.1 1938.55
  3906.2 1936.33  3927.0 1936.51  3976.4 1934.09  4068.8 1934.25  4154.6 1932.17
  4473.2 1928.34  4793.1 1928.49  4823.7 1927.38  4830.0 1927.54  4835.3 1930.54
  4845.2 1934.31  4854.3 1935.68  4884.1 1933.25  4889.4 1931.11  4913.8 1927.74
  5067.2 1927.14  5067.6 1926.64  5072.5 1927.14  5090.6 1927.28  5102.9 1928.46
  5321.5 1928.21  5571.6 1931.52  5690.8 1937.96  5765.5 1937.80  5858.3 1941.72
#Mann=3,-1,0
  3437.9    0.05       0  5067.2    0.05       0  5072.5    0.05       0
Bank Sta=5067.2,5072.5
Exp/Cntr=0.3,0.1

Type RM Length L Ch R = 1,6269,97,97,97
BEGIN DESCRIPTION:
Mapping XS f1eb9b3a
END DESCRIPTION:
XS GIS Cut Line= 6
      1569501.46      6772996.23      1570498.88      6772183.71
      1570702.01      6772102.98      1570759.30      6772006.63
      1570816.59      6771441.52      1570800.97      6771225.37
#Sta/Elev= 30
  3468.2 1947.35  3746.3 1939.95  3846.8 1939.05  3867.7 1936.91  3938.0 1934.87
  4073.8 1934.59  4130.6 1932.17  4442.9 1928.38  4720.8 1928.34  4804.9 1927.03
  4805.3 1926.53  4810.2 1927.03  4830.5 1932.03  4842.7 1937.83  4920.6 1939.45
  4941.9 1937.99  4985.7 1939.38  4993.0 1938.09  5014.1 1939.69  5029.3 1937.20
  5031.8 1939.19  5051.1 1937.70  5072.9 1939.70  5120.5 1935.48  5144.0 1931.55
  5147.9 1929.02  5152.9 1928.30  5190.8 1927.47  5804.1 1933.29  5876.9 1937.75
#Mann=3,-1,0
  3468.2    0.05       0  4804.9    0.05       0  4810.2    0.05       0
Bank Sta=4804.9,4810.2
Exp/Cntr=0.3,0.1

Type RM Length L Ch R = 1,6172,470,470,470
BEGIN DESCRIPTION:
Elm 01 65 6171.555
END DESCRIPTION:
XS GIS Cut Line= 3
      1569604.99      6772988.01      1570810.02      6772088.05
      1571008.00      6771253.72
#Sta/Elev= 30
  3496.0 1945.64  3524.1 1943.78  3718.0 1939.25  3768.1 1939.52  3838.9 1935.76
  3945.3 1934.63  4045.3 1934.79  4103.7 1931.58  4168.3 1931.55  4474.7 1927.76
  4724.9 1927.85  4739.5 1926.72  4789.5 1927.78  4989.6 1927.41  5002.6 1927.14
  5007.7 1925.97  5008.1 1925.47  5013.0 1925.97  5020.6 1927.37  5143.9 1926.86
  5164.5 1927.73  5255.8 1928.21  5287.8 1927.60  5350.5 1928.99  5392.7 1928.11
  5555.0 1930.37  5657.8 1930.68  5678.4 1931.88  5688.2 1931.38  5857.5 1934.63
#Mann=3,-1,0
  3496.0    0.05       0  5007.7    0.05       0  5013.0    0.05       0
Bank Sta=5007.7,5013
Exp/Cntr=0.3,0.1

Type RM Length L Ch R = 1,5702,493,493,493
BEGIN DESCRIPTION:
Elm 01 65 5701.684
END DESCRIPTION:
XS GIS Cut Line= 3
      1569568.73      6773355.37      1571101.46      6772389.46
      1573089.56      6770695.66
#Sta/Elev= 30
  3188.3 1948.02  3358.4 1943.59  3610.4 1941.07  3713.9 1937.64  3786.7 1937.66
  3808.1 1935.59  3835.2 1936.52  4096.5 1931.55  4685.0 1927.18  4692.1 1925.67
  4707.4 1927.12  4945.1 1926.97  4977.8 1924.90  4978.3 1924.40  4983.2 1924.90
  4999.1 1927.79  5017.8 1925.88  5123.7 1925.12  5514.6 1927.12  6017.5 1932.19
  6068.1 1933.82  6351.3 1934.66  6507.3 1937.69  6642.3 1935.73  6769.7 1936.02
  6954.2 1938.75  7046.4 1942.19  7216.6 1943.58  7238.0 1945.01  7611.8 1947.66
#Mann=3,-1,0
  3188.3    0.05       0  4977.8    0.03       0  4983.2    0.05       0
Bank Sta=4977.8,4983.2
Exp/Cntr=0.3,0.1

Type RM Length L Ch R = 1,5209,476,476,476
BEGIN DESCRIPTION:
Elm 01 65 5208.636
END DESCRIPTION:
XS GIS Cut Line= 3
      1569853.44      6773452.60      1571107.05      6772882.16
      1573200.37      6771529.18
#Sta/Elev= 30
  3622.7 1942.80  3778.2 1943.09  3810.3 1940.24  3838.8 1942.98  4011.2 1938.12
  4224.3 1935.29  4391.2 1929.69  4396.7 1930.72  4540.5 1928.99  4547.3 1927.90
  4632.7 1928.64  4843.9 1925.35  4856.8 1926.53  4874.3 1924.93  4879.8 1926.16
  4925.9 1926.58  4999.0 1923.75  5022.1 1926.49  5109.8 1924.89  5128.2 1922.51
  5128.6 1922.01  5133.6 1922.51  5161.3 1924.87  5378.6 1923.94  6128.7 1929.81
  6295.4 1929.89  6593.1 1935.25  6615.3 1934.49  7177.4 1942.16  7492.5 1941.88
#Mann=3,-1,0
  3622.7    0.05       0  5128.2    0.03       0  5133.6    0.05       0
Bank Sta=5128.2,5133.6
Exp/Cntr=0.3,0.1

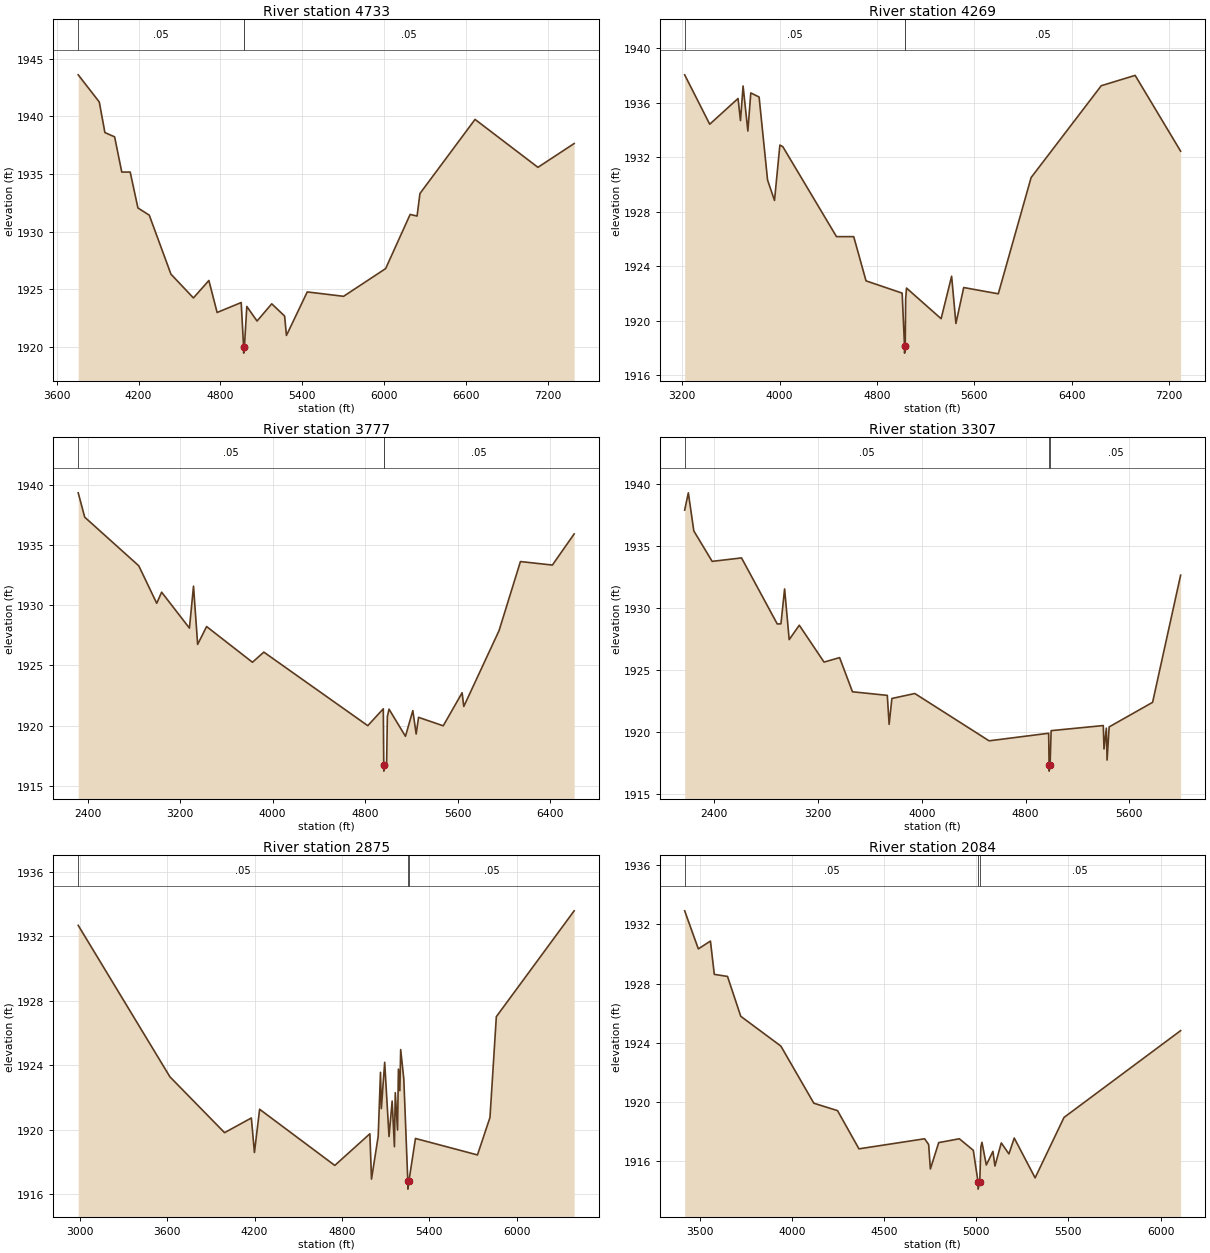
Type RM Length L Ch R = 1,4733,464,464,464
BEGIN DESCRIPTION:
Elm 01 65 4732.582
END DESCRIPTION:
XS GIS Cut Line= 3
      1570155.04      6773537.99      1571361.12      6773240.18
      1573339.61      6771893.53
#Sta/Elev= 30
  3757.7 1943.59  3912.2 1941.24  3953.4 1938.59  4024.6 1938.22  4077.0 1935.17
  4138.8 1935.17  4195.5 1932.06  4278.5 1931.44  4437.5 1926.33  4602.3 1924.27
  4715.6 1925.78  4776.0 1923.01  4952.5 1923.87  4970.3 1919.99  4970.7 1919.49
  4975.9 1919.99  4993.7 1923.53  5068.7 1922.27  5176.4 1923.76  5270.8 1922.70
  5284.2 1921.02  5436.7 1924.79  5703.1 1924.41  6011.4 1926.81  6191.0 1931.50
  6241.8 1931.36  6262.8 1933.31  6666.8 1939.73  7127.7 1935.58  7393.3 1937.64
#Mann=3,-1,0
  3757.7    0.05       0  4970.3    0.05       0  4975.9    0.05       0
Bank Sta=4970.3,4975.9
Exp/Cntr=0.3,0.1

Type RM Length L Ch R = 1,4269,492,492,492
BEGIN DESCRIPTION:
Elm 01 65 4269.49
END DESCRIPTION:
XS GIS Cut Line= 3
      1569721.47      6773935.24      1571481.16      6773665.14
      1573277.07      6772233.84
#Sta/Elev= 30
  3219.7 1938.06  3425.6 1934.43  3658.3 1936.32  3678.5 1934.70  3699.8 1937.24
  3739.2 1933.93  3763.1 1936.73  3831.5 1936.43  3901.1 1930.33  3958.1 1928.83
  4002.3 1932.90  4026.5 1932.78  4467.7 1926.17  4609.3 1926.17  4710.5 1922.92
  5007.4 1922.02  5027.0 1918.11  5027.5 1917.61  5032.6 1918.11  5036.2 1921.60
  5043.3 1922.39  5327.7 1920.14  5414.1 1923.26  5449.4 1919.79  5513.4 1922.43
  5797.7 1921.97  6067.5 1930.51  6644.1 1937.26  6922.7 1938.02  7296.5 1932.45
#Mann=3,-1,0
  3219.7    0.05       0  5027.0    0.03       0  5032.6    0.05       0
Bank Sta=5027,5032.6
Exp/Cntr=0.3,0.1

Type RM Length L Ch R = 1,3777,470,470,470
BEGIN DESCRIPTION:
Elm 01 65 3776.995
END DESCRIPTION:
XS GIS Cut Line= 3
      1569904.99      6775688.01      1571894.51      6773887.33
      1572911.11      6772639.40
#Sta/Elev= 30
  2316.6 1939.32  2373.0 1937.30  2840.8 1933.27  2996.2 1930.16  3038.8 1931.08
  3279.4 1928.10  3314.7 1931.58  3350.4 1926.75  3428.1 1928.23  3824.8 1925.27
  3923.5 1926.11  4823.1 1920.01  4957.6 1921.41  4961.5 1916.74  4962.0 1916.24
  4967.1 1916.74  4986.0 1916.74  4992.7 1920.77  5007.1 1921.38  5149.3 1919.13
  5213.2 1921.26  5242.0 1919.32  5262.8 1920.70  5476.4 1920.00  5639.8 1922.74
  5654.2 1921.60  5959.4 1927.89  6144.6 1933.62  6421.1 1933.33  6609.6 1935.91
#Mann=3,-1,0
  2316.6    0.05       0  4961.5    0.05       0  4967.1    0.05       0
Bank Sta=4961.5,4967.1
Exp/Cntr=0.3,0.1

Type RM Length L Ch R = 1,3307,432,432,432
BEGIN DESCRIPTION:
Elm 01 65 3306.991
END DESCRIPTION:
XS GIS Cut Line= 3
      1570255.02      6775987.98      1572277.02      6774009.83
      1572654.99      6773088.01
#Sta/Elev= 30
  2171.3 1937.87  2199.5 1939.26  2241.9 1936.19  2383.4 1933.74  2609.7 1934.02
  2885.4 1928.70  2913.7 1928.71  2942.0 1931.52  2977.4 1927.44  3055.2 1928.60
  3246.2 1925.63  3366.3 1925.99  3465.4 1923.24  3734.1 1922.95  3748.2 1920.62
  3769.4 1922.70  3946.3 1923.10  4519.1 1919.29  4978.7 1919.90  4981.9 1917.35
  4982.4 1916.85  4989.5 1917.35  4997.7 1920.11  5399.9 1920.52  5405.3 1918.63
  5423.5 1920.31  5429.2 1917.74  5445.1 1920.41  5780.2 1922.39  5996.3 1932.63
#Mann=3,-1,0
  2171.3    0.05       0  4981.9    0.03       0  4989.5    0.05       0
Bank Sta=4981.9,4989.5
Exp/Cntr=0.3,0.1

Type RM Length L Ch R = 1,2875,791,791,791
BEGIN DESCRIPTION:
Elm 01 65 2874.807
END DESCRIPTION:
XS GIS Cut Line= 3
      1570854.98      6775788.02      1572304.67      6774395.86
      1573504.99      6773688.00
#Sta/Elev= 30
  2990.1 1932.68  3619.6 1923.29  3994.4 1919.83  4178.4 1920.74  4199.4 1918.60
  4235.0 1921.28  4751.0 1917.80  4991.6 1919.76  5002.8 1916.95  5048.8 1919.61
  5064.5 1923.57  5070.3 1921.32  5093.3 1924.19  5123.0 1919.59  5144.5 1921.79
  5160.1 1918.96  5165.9 1922.31  5181.6 1919.99  5187.4 1923.77  5197.2 1922.43
  5203.0 1924.98  5224.5 1923.16  5251.9 1916.83  5252.4 1916.33  5259.6 1916.83
  5304.5 1919.47  5730.0 1918.45  5815.8 1920.77  5859.5 1927.02  6393.5 1933.58
#Mann=3,-1,0
  2990.1    0.05       0  5251.9    0.05       0  5259.6    0.05       0
Bank Sta=5251.9,5259.6
Exp/Cntr=0.3,0.1

Type RM Length L Ch R = 1,2084,620,620,620
BEGIN DESCRIPTION:
Mapping XS 25499d00
END DESCRIPTION:
XS GIS Cut Line= 5
      1571254.47      6775812.10      1572205.90      6775155.82
      1572320.48      6775093.32      1572896.87      6774843.32
      1573451.25      6774299.34
#Sta/Elev= 30
  3417.8 1932.92  3492.0 1930.35  3557.6 1930.88  3578.6 1928.63  3650.3 1928.49
  3722.1 1925.80  3939.7 1923.79  4118.8 1919.93  4247.3 1919.43  4363.6 1916.85
  4720.0 1917.53  4741.8 1917.14  4751.2 1915.49  4796.3 1917.27  4908.4 1917.53
  4984.2 1916.75  5009.5 1914.63  5010.0 1914.13  5019.1 1914.63  5025.2 1916.98
  5031.1 1917.29  5054.6 1915.76  5090.6 1916.68  5101.5 1915.69  5135.9 1917.25
  5177.4 1916.51  5206.3 1917.58  5319.5 1914.89  5476.3 1918.97  6109.1 1924.83
#Mann=3,-1,0
  3417.8    0.05       0  5009.5    0.05       0  5019.1    0.05       0
Bank Sta=5009.5,5019.1
Exp/Cntr=0.3,0.1