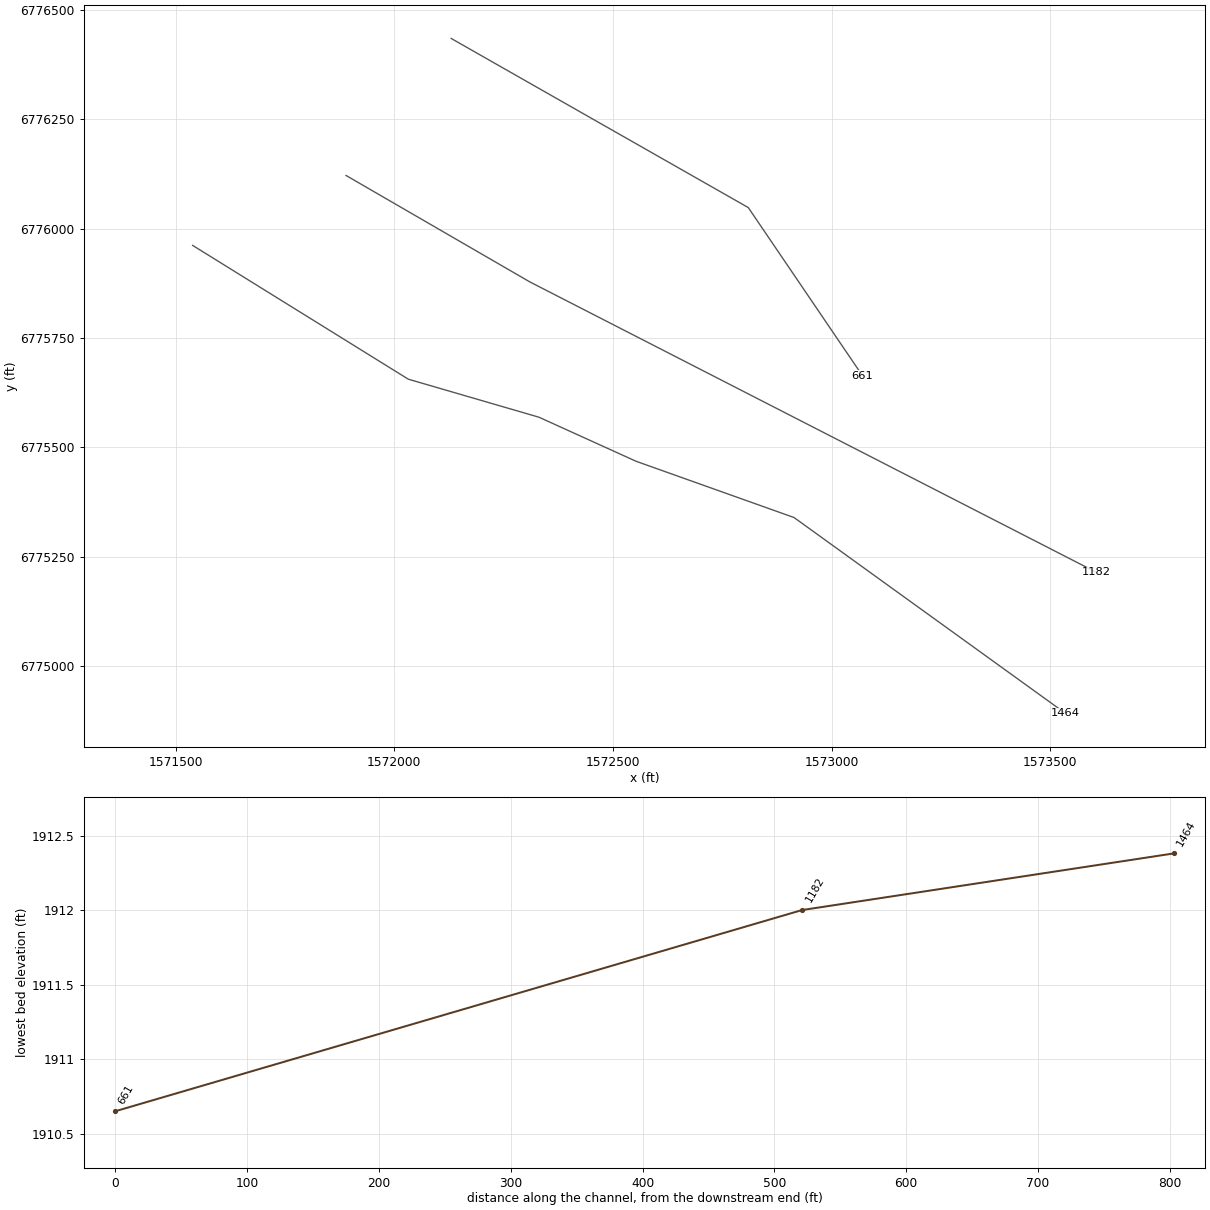
HEC-RAS study Elm 01 65.prj: Elm 01 65 Base Level Engineering

--- Elm 01 65.g01 (geometry) --- (continued)

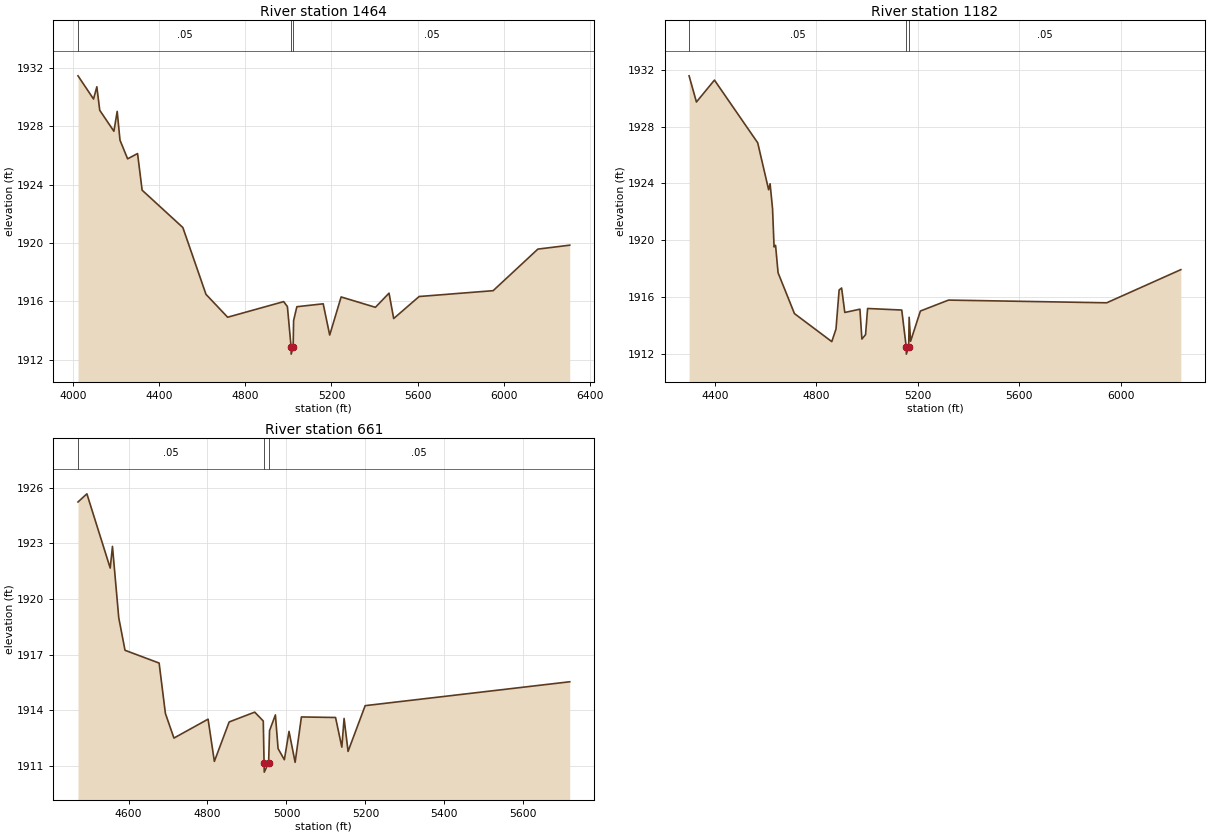
Type RM Length L Ch R = 1,1464,282,282,282
BEGIN DESCRIPTION:
Mapping XS 69da27cb
END DESCRIPTION:
XS GIS Cut Line= 6
      1571539.25      6775961.37      1572032.29      6775655.82
      1572330.90      6775569.02      1572553.12      6775468.32
      1572914.23      6775339.85      1573535.05      6774892.44
#Sta/Elev= 30
  4023.3 1931.46  4095.4 1929.87  4110.8 1930.71  4124.2 1929.10  4190.0 1927.66
  4205.3 1929.02  4218.3 1927.05  4253.7 1925.77  4299.9 1926.13  4321.1 1923.62
  4510.2 1921.06  4617.6 1916.48  4718.2 1914.91  4978.3 1915.98  4995.7 1915.64
  5012.8 1912.88  5013.3 1912.38  5022.4 1912.88  5024.5 1914.68  5039.6 1915.63
  5161.9 1915.83  5192.1 1913.69  5245.2 1916.30  5404.4 1915.59  5467.6 1916.56
  5489.3 1914.82  5607.4 1916.33  5951.1 1916.73  6158.8 1919.58  6306.8 1919.85
#Mann=3,-1,0
  4023.3    0.05       0  5012.8    0.05       0  5022.4    0.05       0
Bank Sta=5012.8,5022.4
Exp/Cntr=0.3,0.1

Type RM Length L Ch R = 1,1182,521,521,521
BEGIN DESCRIPTION:
Elm 01 65 2405.541
END DESCRIPTION:
XS GIS Cut Line= 3
      1571889.91      6776121.11      1572310.06      6775878.05
      1573605.24      6775214.83
#Sta/Elev= 30
  4297.4 1931.57  4326.4 1929.73  4397.5 1931.27  4568.2 1926.86  4611.3 1923.56
  4617.1 1923.98  4626.8 1922.21  4632.8 1919.54  4638.6 1919.65  4648.6 1917.72
  4713.2 1914.85  4860.5 1912.88  4877.1 1913.76  4889.5 1916.51  4899.3 1916.65
  4911.9 1914.93  4971.6 1915.16  4979.3 1913.06  4993.8 1913.37  5001.8 1915.21
  5136.6 1915.10  5154.3 1912.50  5154.8 1912.00  5163.9 1912.50  5165.8 1914.59
  5171.4 1912.90  5210.2 1915.03  5321.2 1915.80  5945.5 1915.61  6237.9 1917.94
#Mann=3,-1,0
  4297.4    0.05       0  5154.3    0.03       0  5163.9    0.05       0
Bank Sta=5154.3,5163.9
Exp/Cntr=0.3,0.1

Type RM Length L Ch R = 1,661,0,0,0
BEGIN DESCRIPTION:
Elm 01 65 1953.381
END DESCRIPTION:
XS GIS Cut Line= 3
      1572130.35      6776434.05      1572809.63      6776047.75
      1573070.57      6775663.89
#Sta/Elev= 30
  4472.0 1925.24  4494.5 1925.68  4553.6 1921.67  4559.3 1922.84  4575.2 1918.99
  4591.1 1917.23  4677.5 1916.54  4693.4 1913.82  4715.0 1912.49  4801.5 1913.51
  4817.4 1911.23  4854.9 1913.36  4919.7 1913.89  4941.3 1913.41  4943.3 1911.15
  4943.8 1910.65  4954.8 1911.15  4957.2 1912.89  4972.0 1913.74  4978.8 1911.92
  4994.7 1911.32  5006.5 1912.85  5022.0 1911.18  5037.9 1913.63  5124.4 1913.60
  5140.3 1912.00  5146.0 1913.55  5156.1 1911.77  5199.4 1914.24  5717.6 1915.53
#Mann=3,-1,0
  4472.0    0.05       0  4943.3    0.05       0  4954.8    0.05       0
Bank Sta=4943.3,4954.8
Exp/Cntr=0.3,0.1

Chan Stop Cuts=-1