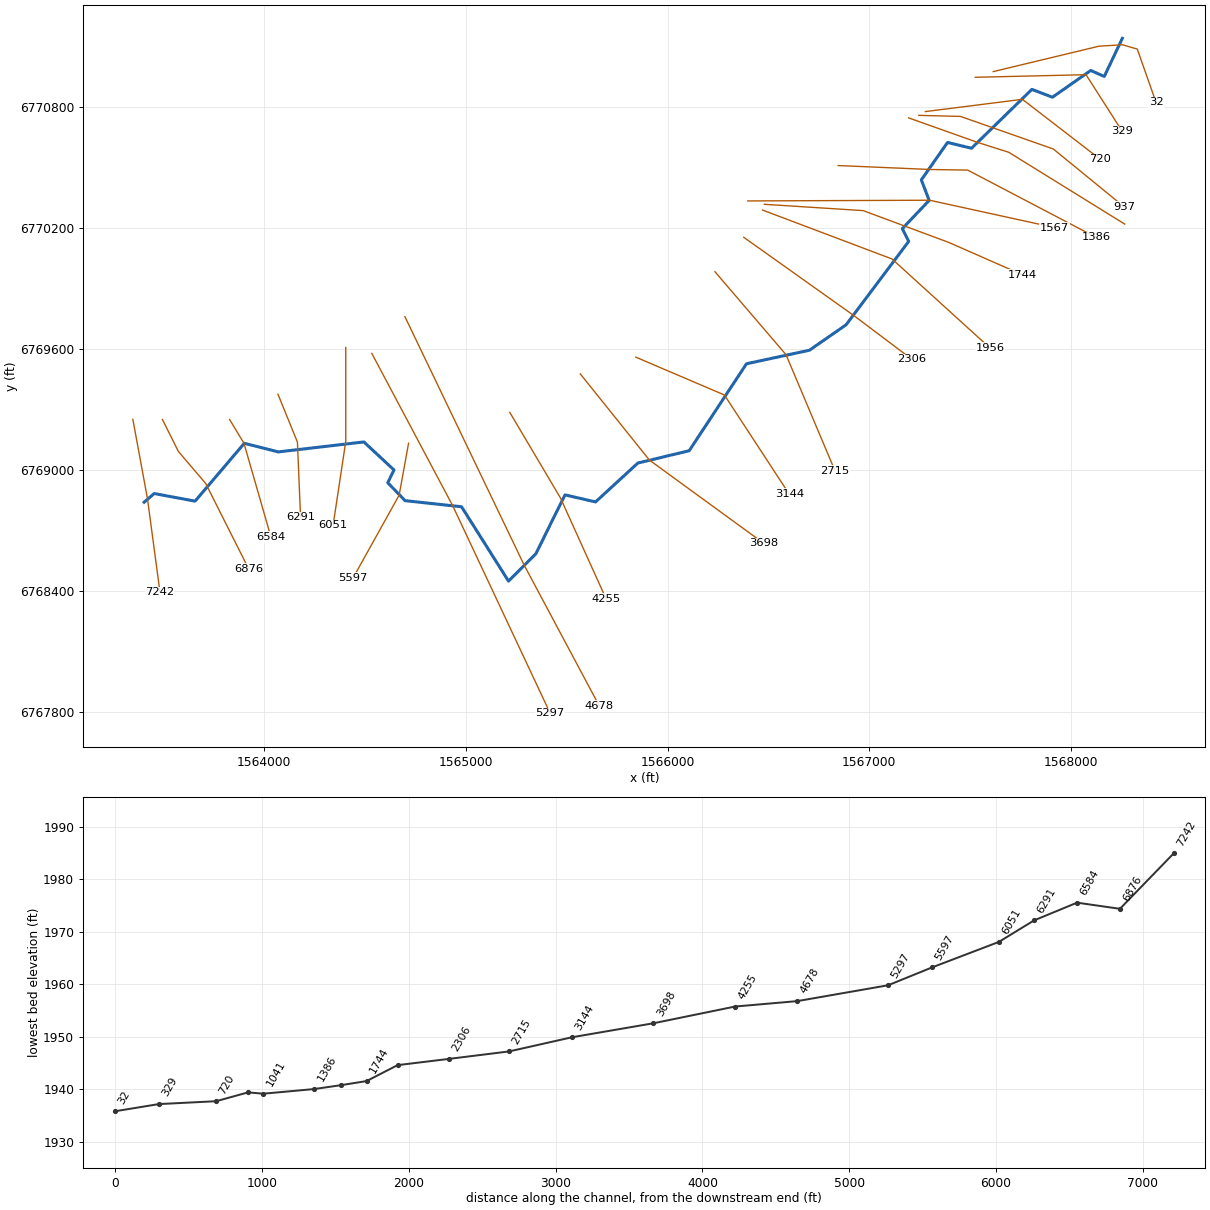
--- Elm 01 66.prj (project) ---

Proj Title=Elm 01 66 Base Level Engineering
Current Plan=p01
Default Exp/Contr=0.3,0.1
English Units
Geom File=g01
Flow File=f01
Plan File=p01
BEGIN DESCRIPTION:
Elm 01 66
END DESCRIPTION:

--- Elm 01 66.p01 (plan) ---

Plan Title=Multiple Run
Short Identifier=Multiple
Geom File=g01
Flow File=f01
Subcritical Flow
K Sum by GR= 0
Std Step Tol= 0.01
Critical Tol= 0.01
Num of Std Step Trials= 20
Max Error Tol= 0.3
Flow Tol Ratio= 0.001
Split Flow NTrial= 30
Split Flow Tol= 0.02
Split Flow Ratio= 0.02
Log Output Level= 0
Friction Slope Method= 1
Unsteady Friction Slope Method= 2
Unsteady Bridges Friction Slope Method= 1
Parabolic Critical Depth
Global Vel Dist=  1 , 1 , 1
Global Log Level= 0
CheckData=True
Encroach Param= -1, 0, 0, 0
BEGIN DESCRIPTION:
Multiple Run
END DESCRIPTION:

--- Elm 01 66.f01 (steady flow) ---

Flow Title=Multiple
Number of Profiles=7
Profile Names=10-year,25-year,50-year,1pct_min,100-year,1pct_plu,500-year
River Rch & RM= Elm 01 66,Reach-1,7242
     108     141     167     123     197     272     278
Boundary for River Rch & Prof#=Elm 01 66,Reach-1,1
Up Type=0
Dn Type=3
Dn Slope=0.001
Boundary for River Rch & Prof#=Elm 01 66,Reach-1,2
Up Type=0
Dn Type=3
Dn Slope=0.001
Boundary for River Rch & Prof#=Elm 01 66,Reach-1,3
Up Type=0
Dn Type=3
Dn Slope=0.001
Boundary for River Rch & Prof#=Elm 01 66,Reach-1,4
Up Type=0
Dn Type=3
Dn Slope=0.001
Boundary for River Rch & Prof#=Elm 01 66,Reach-1,5
Up Type=0
Dn Type=3
Dn Slope=0.001
Boundary for River Rch & Prof#=Elm 01 66,Reach-1,6
Up Type=0
Dn Type=3
Dn Slope=0.001
Boundary for River Rch & Prof#=Elm 01 66,Reach-1,7
Up Type=0
Dn Type=3
Dn Slope=0.001

--- Elm 01 66.g01 (geometry) ---

Geom Title=Existing Conditions

River Reach=Elm 01 66,Reach-1
Reach XY= 30
      1563405.00      6768838.00      1563454.86      6768881.09
      1563657.68      6768843.39      1563901.57      6769130.21
      1564070.16      6769087.53      1564494.57      6769136.95
      1564643.76      6768998.00      1564613.00      6768934.65
      1564698.77      6768845.82      1564978.71      6768815.64
      1565211.66      6768446.95      1565346.88      6768581.95
      1565491.62      6768874.47      1565643.12      6768839.53
      1565852.71      6769032.16      1566107.46      6769093.46
      1566391.44      6769524.54      1566703.50      6769591.62
      1566885.16      6769717.61      1567195.68      6770131.34
      1567164.30      6770194.67      1567297.18      6770334.59
      1567258.37      6770436.26      1567388.26      6770621.71
      1567507.29      6770593.12      1567806.44      6770884.90
      1567908.31      6770846.07      1568098.35      6770978.68
      1568165.32      6770949.11      1568255.00      6771138.00

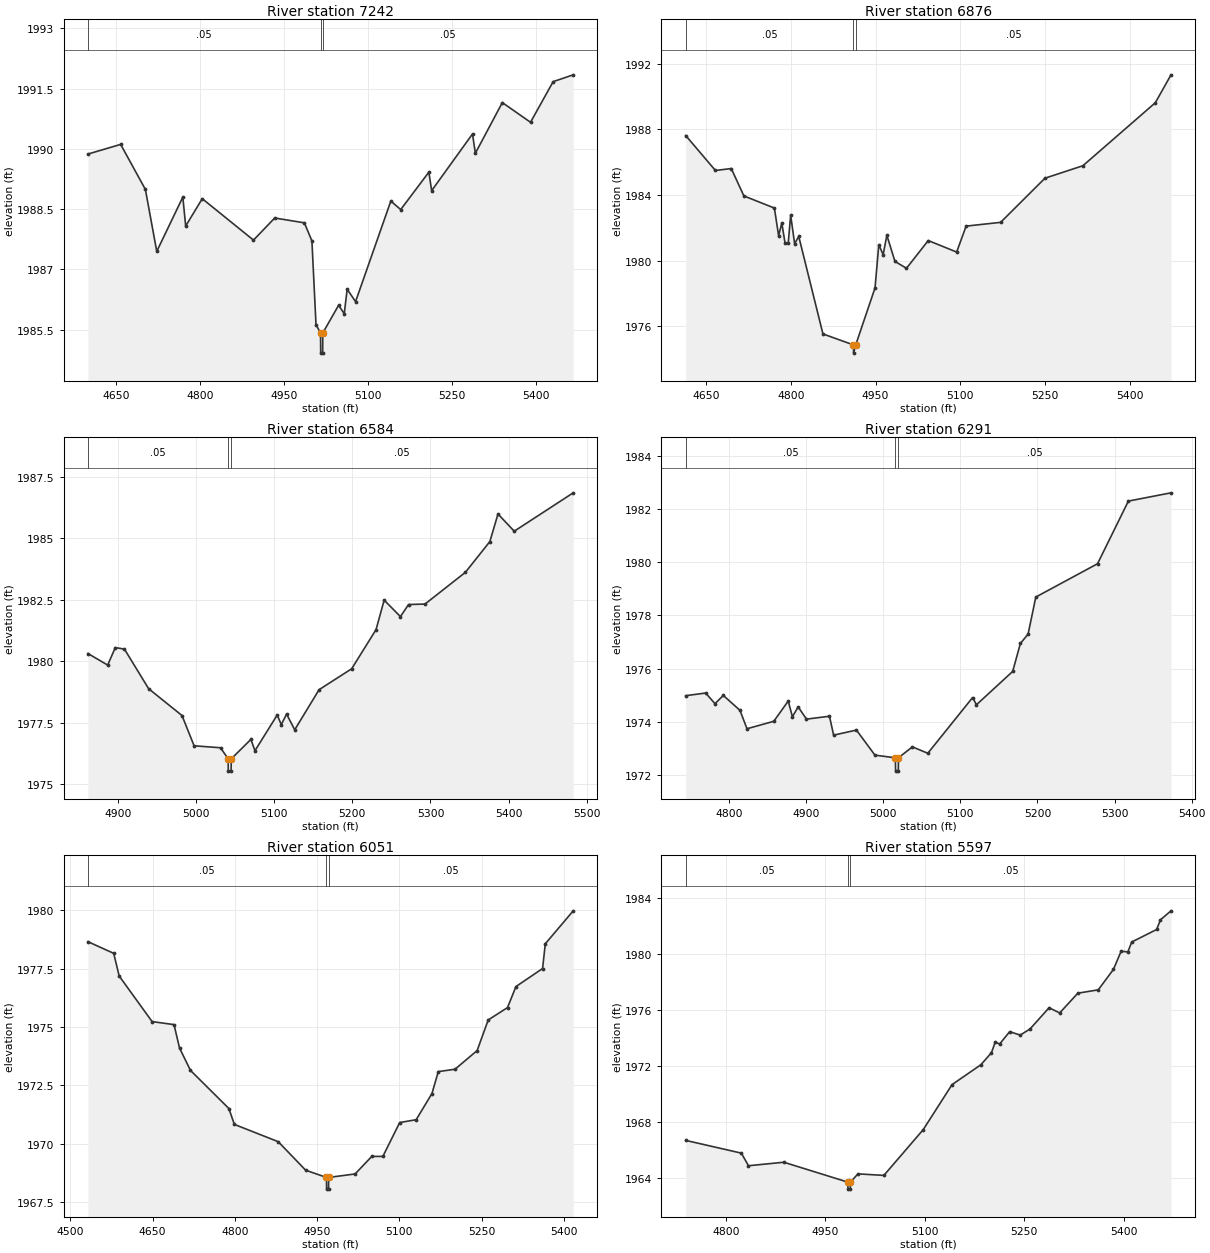
Type RM Length L Ch R = 1,7242,366,366,366
BEGIN DESCRIPTION:
Elm 01 66 7010.422
END DESCRIPTION:
XS GIS Cut Line= 3
      1563349.11      6769248.96      1563421.63      6768855.29
      1563483.57      6768392.41
#Sta/Elev= 30
  4599.7 1989.87  4658.2 1990.11  4702.4 1988.99  4722.7 1987.45  4769.3 1988.80
  4774.4 1988.08  4804.0 1988.76  4895.6 1987.73  4933.5 1988.28  4986.5 1988.16
  5000.0 1987.71  5007.3 1985.63  5015.4 1985.42  5015.7 1984.92  5019.2 1984.92
  5019.4 1985.42  5047.7 1986.11  5057.8 1985.90  5063.0 1986.51  5078.0 1986.20
  5141.0 1988.70  5158.7 1988.49  5209.0 1989.42  5214.0 1988.96  5287.0 1990.37
  5292.1 1989.89  5340.3 1991.15  5390.7 1990.66  5431.1 1991.67  5467.0 1991.84
#Mann=3,-1,0
  4599.7    0.05       0  5015.4    0.05       0  5019.4    0.05       0
Bank Sta=5015.4,5019.4
Exp/Cntr=0.3,0.1

Type RM Length L Ch R = 1,6876,292,292,292
BEGIN DESCRIPTION:
Elm 01 66 6875.78
END DESCRIPTION:
XS GIS Cut Line= 4
      1563495.63      6769248.36      1563575.06      6769089.50
      1563710.48      6768930.65      1563922.71      6768508.77
#Sta/Elev= 30
  4614.2 1987.63  4666.8 1985.50  4694.8 1985.62  4717.1 1983.95  4771.1 1983.21
  4778.6 1981.52  4784.2 1982.30  4789.9 1981.09  4795.6 1981.09  4799.9 1982.77
  4806.9 1981.04  4814.2 1981.48  4857.0 1975.54  4911.0 1974.87  4911.2 1974.37
  4915.0 1974.87  4949.2 1978.35  4955.8 1980.98  4963.5 1980.37  4970.1 1981.55
  4984.4 1979.96  5004.8 1979.54  5043.3 1981.23  5093.6 1980.53  5110.3 1982.11
  5171.4 1982.34  5249.8 1985.03  5316.9 1985.79  5445.1 1989.63  5472.8 1991.33
#Mann=3,-1,0
  4614.2    0.05       0  4911.0    0.05       0  4915.0    0.05       0
Bank Sta=4911,4915
Exp/Cntr=0.3,0.1

Type RM Length L Ch R = 1,6584,293,293,293
BEGIN DESCRIPTION:
Elm 01 66 6584.21
END DESCRIPTION:
XS GIS Cut Line= 3
      1563828.94      6769247.96      1563900.15      6769129.87
      1564033.84      6768665.43
#Sta/Elev= 30
  4861.5 1980.32  4886.8 1979.85  4896.5 1980.56  4908.2 1980.50  4939.2 1978.89
  4981.9 1977.80  4997.4 1976.57  5031.2 1976.49  5041.0 1976.04  5041.2 1975.54
  5044.7 1975.54  5045.0 1976.04  5070.1 1976.83  5075.3 1976.37  5103.8 1977.82
  5109.0 1977.43  5115.8 1977.86  5126.2 1977.22  5157.4 1978.85  5199.1 1979.70
  5230.3 1981.29  5240.7 1982.49  5261.5 1981.82  5271.9 1982.31  5293.0 1982.33
  5344.7 1983.62  5376.0 1984.87  5386.4 1985.99  5407.2 1985.29  5482.7 1986.85
#Mann=3,-1,0
  4861.5    0.05       0  5041.0    0.05       0  5045.0    0.05       0
Bank Sta=5041,5045
Exp/Cntr=0.3,0.1

Type RM Length L Ch R = 1,6291,240,240,240
BEGIN DESCRIPTION:
Elm 01 66 6290.6
END DESCRIPTION:
XS GIS Cut Line= 3
      1564068.67      6769373.18      1564165.01      6769136.23
      1564180.63      6768762.75
#Sta/Elev= 30
  4743.6 1974.99  4769.5 1975.09  4781.6 1974.69  4792.4 1975.00  4814.0 1974.44
  4823.1 1973.75  4857.9 1974.03  4876.6 1974.79  4882.0 1974.20  4889.5 1974.57
  4900.3 1974.11  4930.1 1974.22  4935.5 1973.51  4965.1 1973.70  4989.1 1972.76
  5015.6 1972.66  5015.9 1972.16  5019.4 1972.16  5019.6 1972.66  5037.7 1973.07
  5057.7 1972.83  5115.8 1974.92  5120.8 1974.65  5167.8 1975.90  5177.8 1976.95
  5187.8 1977.30  5197.8 1978.69  5277.9 1979.94  5317.9 1982.29  5373.2 1982.60
#Mann=3,-1,0
  4743.6    0.05       0  5015.6    0.05       0  5019.6    0.05       0
Bank Sta=5015.6,5019.6
Exp/Cntr=0.3,0.1

Type RM Length L Ch R = 1,6051,454,454,454
BEGIN DESCRIPTION:
Elm 01 66 6050.98
END DESCRIPTION:
XS GIS Cut Line= 3
      1564404.59      6769604.98      1564404.59      6769138.84
      1564342.09      6768724.77
#Sta/Elev= 30
  4532.1 1978.65  4579.1 1978.15  4589.1 1977.18  4649.1 1975.23  4689.1 1975.10
  4699.1 1974.10  4719.1 1973.14  4789.1 1971.51  4799.1 1970.83  4879.1 1970.09
  4929.1 1968.87  4967.1 1968.56  4967.3 1968.06  4970.8 1968.06  4971.1 1968.56
  5019.3 1968.71  5049.7 1969.46  5069.9 1969.46  5100.6 1970.91  5130.6 1971.03
  5159.4 1972.15  5171.0 1973.09  5201.4 1973.19  5241.8 1973.99  5262.0 1975.30
  5297.2 1975.83  5312.6 1976.73  5361.1 1977.50  5366.1 1978.56  5417.0 1979.97
#Mann=3,-1,0
  4532.1    0.05       0  4967.1    0.05       0  4971.1    0.05       0
Bank Sta=4967.1,4971.1
Exp/Cntr=0.3,0.1

Type RM Length L Ch R = 1,5597,300,300,300
BEGIN DESCRIPTION:
Elm 01 66 5596.88
END DESCRIPTION:
XS GIS Cut Line= 3
      1564716.13      6769130.56      1564669.26      6768872.78
      1564440.58      6768462.18
#Sta/Elev= 30
  4739.3 1966.70  4823.2 1965.79  4834.0 1964.89  4887.3 1965.14  4983.8 1963.72
  4984.1 1963.22  4987.6 1963.22  4987.8 1963.72  4999.1 1964.31  5038.2 1964.20
  5097.6 1967.47  5141.0 1970.68  5184.5 1972.10  5200.5 1972.96  5206.2 1973.72
  5212.8 1973.58  5227.9 1974.46  5243.9 1974.22  5258.6 1974.65  5287.4 1976.17
  5303.4 1975.80  5330.8 1977.21  5361.6 1977.45  5384.5 1978.91  5396.0 1980.20
  5406.3 1980.16  5412.0 1980.86  5449.7 1981.76  5455.4 1982.45  5471.3 1983.09
#Mann=3,-1,0
  4739.3    0.05       0  4983.8    0.05       0  4987.8    0.05       0
Bank Sta=4983.8,4987.8
Exp/Cntr=0.3,0.1

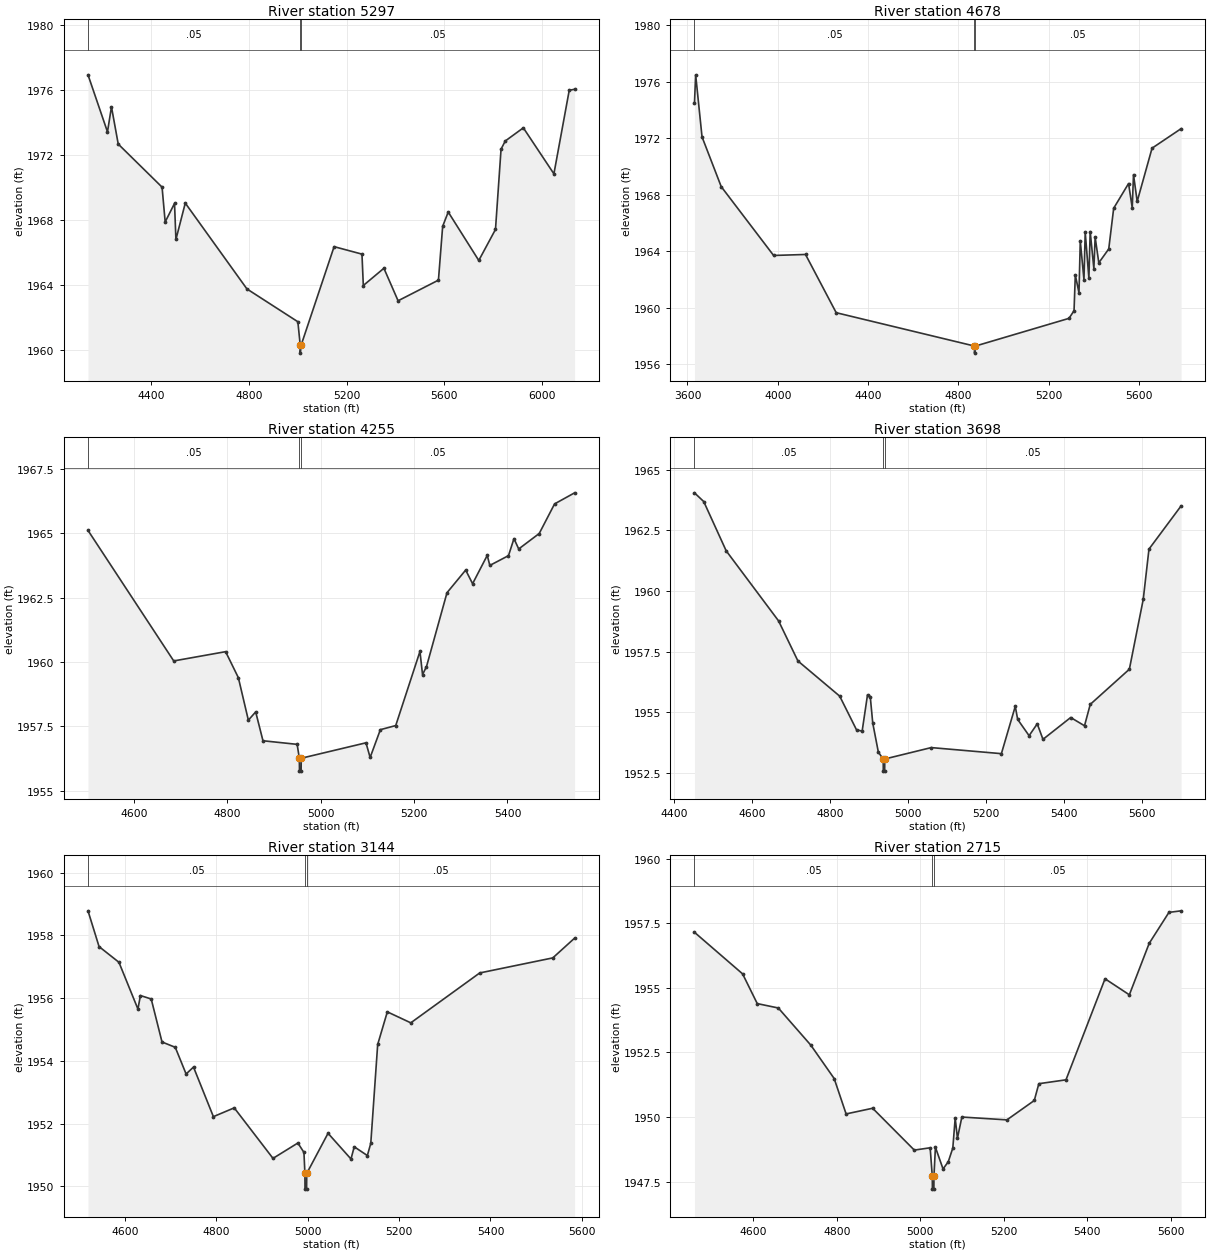
Type RM Length L Ch R = 1,5297,619,619,619
BEGIN DESCRIPTION:
Elm 01 66 5296.5
END DESCRIPTION:
XS GIS Cut Line= 3
      1564533.84      6769575.91      1564934.89      6768820.70
      1565418.44      6767791.20
#Sta/Elev= 30
  4141.2 1976.93  4221.0 1973.42  4237.3 1974.96  4265.0 1972.67  4444.5 1970.02
  4457.2 1967.88  4495.5 1969.02  4501.2 1966.80  4539.5 1969.04  4791.9 1963.76
  5000.5 1961.74  5010.1 1960.31  5010.3 1959.81  5014.1 1960.31  5148.9 1966.36
  5263.0 1965.90  5268.5 1963.97  5352.8 1965.03  5410.9 1963.03  5576.1 1964.30
  5593.4 1967.61  5616.2 1968.49  5741.3 1965.51  5809.7 1967.42  5832.5 1972.36
  5849.8 1972.86  5923.7 1973.67  6048.9 1970.84  6111.7 1975.98  6133.7 1976.04
#Mann=3,-1,0
  4141.2    0.05       0  5010.1    0.05       0  5014.1    0.05       0
Bank Sta=5010.1,5014.1
Exp/Cntr=0.3,0.1

Type RM Length L Ch R = 1,4678,423,423,423
BEGIN DESCRIPTION:
Elm 01 66 4677.73
END DESCRIPTION:
XS GIS Cut Line= 3
      1564697.91      6769758.20      1565289.06      6768526.42
      1565660.73      6767829.87
#Sta/Elev= 30
  3630.9 1974.46  3636.2 1976.48  3664.4 1972.09  3749.4 1968.57  3981.5 1963.70
  4122.9 1963.77  4258.8 1959.65  4871.4 1957.29  4871.7 1956.79  4875.4 1957.29
  5290.1 1959.25  5312.5 1959.79  5318.1 1962.32  5334.4 1961.06  5340.1 1964.73
  5356.4 1961.99  5362.0 1965.34  5378.3 1962.09  5384.0 1965.39  5400.3 1962.77
  5406.0 1964.99  5422.2 1963.18  5466.2 1964.16  5488.1 1967.04  5554.0 1968.79
  5570.3 1967.07  5575.9 1969.42  5592.2 1967.52  5658.1 1971.29  5786.7 1972.67
#Mann=3,-1,0
  3630.9    0.05       0  4871.4    0.05       0  4875.4    0.05       0
Bank Sta=4871.4,4875.4
Exp/Cntr=0.3,0.1

Type RM Length L Ch R = 1,4255,557,557,557
BEGIN DESCRIPTION:
Elm 01 66 4254.57
END DESCRIPTION:
XS GIS Cut Line= 3
      1565218.00      6769283.48      1565469.76      6768858.09
      1565695.46      6768358.95
#Sta/Elev= 30
  4501.7 1965.11  4685.3 1960.04  4796.4 1960.40  4823.7 1959.39  4845.1 1957.74
  4860.8 1958.06  4876.4 1956.94  4949.6 1956.80  4954.3 1956.26  4954.6 1955.76
  4958.1 1955.76  4958.3 1956.26  5097.0 1956.86  5105.9 1956.29  5127.8 1957.37
  5160.7 1957.53  5212.6 1960.41  5218.1 1959.51  5226.6 1959.82  5270.5 1962.69
  5310.5 1963.57  5325.3 1963.04  5356.7 1964.14  5362.2 1963.75  5402.2 1964.13
  5413.9 1964.79  5424.1 1964.39  5468.0 1964.99  5500.9 1966.14  5543.8 1966.57
#Mann=3,-1,0
  4501.7    0.05       0  4954.3    0.05       0  4958.3    0.05       0
Bank Sta=4954.3,4958.3
Exp/Cntr=0.3,0.1

Type RM Length L Ch R = 1,3698,554,554,554
BEGIN DESCRIPTION:
Elm 01 66 3697.65
END DESCRIPTION:
XS GIS Cut Line= 3
      1565567.39      6769474.44      1565910.29      6769046.90
      1566476.74      6768634.54
#Sta/Elev= 30
  4451.9 1964.04  4475.7 1963.68  4533.3 1961.65  4667.8 1958.76  4717.4 1957.11
  4824.6 1955.66  4867.8 1954.27  4882.2 1954.22  4896.0 1955.72  4903.0 1955.64
  4909.4 1954.55  4923.8 1953.35  4936.2 1953.07  4936.5 1952.57  4940.0 1952.57
  4940.2 1953.07  5059.5 1953.54  5239.5 1953.29  5275.1 1955.24  5281.3 1954.70
  5310.6 1954.03  5331.5 1954.52  5346.2 1953.88  5417.3 1954.78  5452.8 1954.44
  5467.5 1955.32  5567.9 1956.77  5603.5 1959.65  5618.2 1961.72  5700.6 1963.50
#Mann=3,-1,0
  4451.9    0.05       0  4936.2    0.05       0  4940.2    0.05       0
Bank Sta=4936.2,4940.2
Exp/Cntr=0.3,0.1

Type RM Length L Ch R = 1,3144,429,429,429
BEGIN DESCRIPTION:
Elm 01 66 3143.54
END DESCRIPTION:
XS GIS Cut Line= 3
      1565842.76      6769557.27      1566281.97      6769369.78
      1566603.13      6768878.50
#Sta/Elev= 30
  4519.6 1958.78  4543.8 1957.64  4587.3 1957.14  4628.8 1955.65  4634.3 1956.08
  4657.9 1955.97  4681.5 1954.60  4710.5 1954.43  4734.2 1953.58  4750.4 1953.80
  4793.9 1952.22  4839.5 1952.50  4924.3 1950.89  4978.7 1951.38  4992.0 1951.08
  4994.1 1950.41  4994.3 1949.91  4997.8 1949.91  4998.1 1950.41  5044.7 1951.69
  5094.9 1950.87  5102.0 1951.26  5130.7 1950.98  5138.2 1951.37  5153.3 1954.52
  5174.4 1955.56  5225.7 1955.21  5376.5 1956.80  5536.4 1957.28  5584.1 1957.91
#Mann=3,-1,0
  4519.6    0.05       0  4994.1    0.05       0  4998.1    0.05       0
Bank Sta=4994.1,4998.1
Exp/Cntr=0.3,0.1

Type RM Length L Ch R = 1,2715,409,409,409
BEGIN DESCRIPTION:
Elm 01 66 2715.1
END DESCRIPTION:
XS GIS Cut Line= 3
      1566235.11      6769980.88      1566587.52      6769569.44
      1566830.28      6768993.77
#Sta/Elev= 30
  4458.6 1957.15  4574.0 1955.54  4609.1 1954.39  4659.6 1954.22  4737.6 1952.78
  4793.5 1951.49  4822.1 1950.12  4885.7 1950.34  4985.6 1948.72  5023.6 1948.81
  5028.7 1947.71  5029.0 1947.21  5032.5 1947.21  5032.7 1947.71  5036.2 1948.83
  5054.5 1947.99  5067.0 1948.27  5077.9 1948.80  5083.6 1949.96  5089.0 1949.18
  5099.6 1950.00  5207.6 1949.89  5273.2 1950.64  5284.1 1951.29  5349.2 1951.44
  5442.8 1955.35  5501.1 1954.73  5548.6 1956.72  5596.0 1957.92  5625.1 1957.98
#Mann=3,-1,0
  4458.6    0.05       0  5028.7    0.05       0  5032.7    0.05       0
Bank Sta=5028.7,5032.7
Exp/Cntr=0.3,0.1

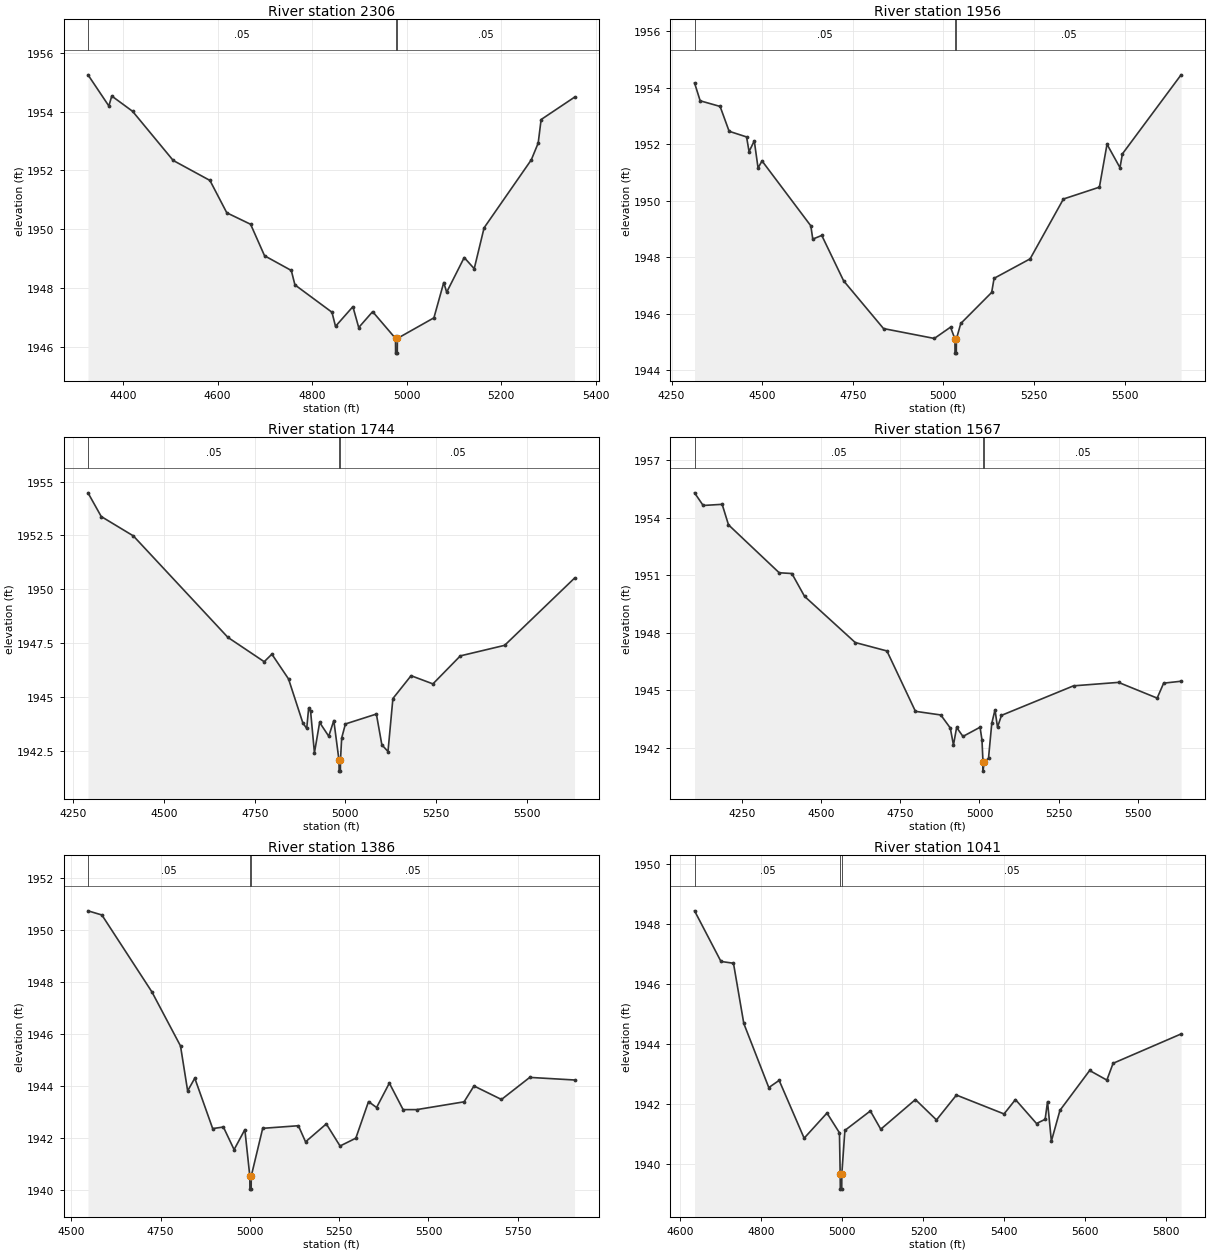
Type RM Length L Ch R = 1,2306,350,350,350
BEGIN DESCRIPTION:
Elm 01 66 2306
END DESCRIPTION:
XS GIS Cut Line= 3
      1566378.06      6770151.47      1566924.91      6769762.61
      1567211.52      6769546.78
#Sta/Elev= 30
  4325.7 1955.25  4369.9 1954.19  4376.0 1954.53  4420.1 1954.01  4506.0 1952.34
  4583.8 1951.66  4619.5 1950.56  4669.9 1950.17  4699.4 1949.10  4756.0 1948.60
  4763.7 1948.11  4842.1 1947.18  4849.6 1946.70  4886.4 1947.37  4898.7 1946.66
  4928.2 1947.20  4976.6 1946.29  4976.8 1945.79  4980.3 1945.79  4980.6 1946.29
  5057.9 1946.99  5078.7 1948.19  5084.9 1947.86  5122.0 1949.04  5143.2 1948.66
  5164.1 1950.05  5264.0 1952.36  5278.6 1952.93  5284.8 1953.73  5355.5 1954.49
#Mann=3,-1,0
  4325.7    0.05       0  4976.6    0.05       0  4980.6    0.05       0
Bank Sta=4976.6,4980.6
Exp/Cntr=0.3,0.1

Type RM Length L Ch R = 1,1956,212,212,212
BEGIN DESCRIPTION:
Elm 01 66 1877.66
END DESCRIPTION:
XS GIS Cut Line= 3
      1566470.81      6770286.72      1567113.20      6770044.05
      1567598.47      6769602.93
#Sta/Elev= 30
  4313.3 1954.17  4328.8 1953.54  4383.8 1953.34  4408.7 1952.46  4456.8 1952.26
  4463.7 1951.74  4478.1 1952.12  4488.5 1951.16  4499.5 1951.41  4634.1 1949.11
  4639.5 1948.64  4664.3 1948.77  4724.7 1947.16  4834.7 1945.47  4974.9 1945.12
  5019.6 1945.52  5031.8 1945.10  5032.0 1944.60  5035.5 1944.60  5035.8 1945.10
  5047.9 1945.65  5133.1 1946.75  5139.8 1947.25  5239.2 1947.94  5331.1 1950.06
  5430.4 1950.48  5451.4 1952.00  5487.2 1951.17  5493.9 1951.66  5655.8 1954.46
#Mann=3,-1,0
  4313.3    0.05       0  5031.8    0.03       0  5035.8    0.05       0
Bank Sta=5031.8,5035.8
Exp/Cntr=0.3,0.1

Type RM Length L Ch R = 1,1744,177,177,177
BEGIN DESCRIPTION:
Mapping XS 48ba1365
END DESCRIPTION:
XS GIS Cut Line= 4
      1566480.30      6770315.11      1566969.86      6770283.87
      1567395.21      6770125.88      1567758.02      6769966.17
#Sta/Elev= 30
  4290.6 1954.48  4327.1 1953.38  4415.6 1952.48  4676.1 1947.77  4776.2 1946.64
  4797.3 1946.99  4843.2 1945.84  4882.6 1943.80  4893.3 1943.54  4898.6 1944.48
  4904.0 1944.34  4914.6 1942.41  4928.9 1943.82  4954.0 1943.18  4968.0 1943.91
  4982.3 1942.06  4982.6 1941.56  4986.1 1941.56  4986.3 1942.06  4989.7 1943.10
  5000.0 1943.75  5085.3 1944.21  5100.4 1942.78  5117.3 1942.47  5130.8 1944.93
  5180.9 1945.99  5241.1 1945.61  5316.6 1946.91  5438.7 1947.40  5631.3 1950.52
#Mann=3,-1,0
  4290.6    0.05       0  4982.3    0.05       0  4986.3    0.05       0
Bank Sta=4982.3,4986.3
Exp/Cntr=0.3,0.1

Type RM Length L Ch R = 1,1567,181,181,181
BEGIN DESCRIPTION:
Elm 01 66 1566.82
END DESCRIPTION:
XS GIS Cut Line= 3
      1566397.89      6770331.87      1567298.92      6770335.34
      1567918.76      6770199.91
#Sta/Elev= 30
  4100.9 1955.29  4128.0 1954.63  4188.0 1954.69  4208.0 1953.62  4368.0 1951.12
  4408.0 1951.08  4448.0 1949.89  4608.0 1947.48  4708.0 1947.04  4798.0 1943.89
  4878.0 1943.70  4908.0 1943.02  4918.0 1942.13  4928.0 1943.05  4948.0 1942.58
  5001.9 1943.06  5008.0 1942.40  5011.1 1941.27  5011.3 1940.77  5015.1 1941.27
  5028.6 1941.44  5038.9 1943.26  5049.1 1943.97  5057.0 1943.06  5069.6 1943.68
  5296.9 1945.22  5438.9 1945.40  5560.9 1944.58  5581.4 1945.36  5636.4 1945.46
#Mann=3,-1,0
  4100.9    0.05       0  5011.1    0.05       0  5015.1    0.05       0
Bank Sta=5011.1,5015.1
Exp/Cntr=0.3,0.1

Type RM Length L Ch R = 1,1386,345,345,345
BEGIN DESCRIPTION:
Elm 01 66 1386.03
END DESCRIPTION:
XS GIS Cut Line= 4
      1566846.13      6770507.30      1567301.90      6770487.77
      1567488.13      6770484.74      1568126.09      6770150.63
#Sta/Elev= 30
  4546.5 1950.75  4585.4 1950.59  4725.5 1947.63  4805.6 1945.55  4825.6 1943.82
  4845.6 1944.31  4895.7 1942.37  4925.7 1942.43  4955.7 1941.56  4985.8 1942.33
  4999.7 1940.54  5000.0 1940.04  5003.5 1940.04  5003.7 1940.54  5035.8 1942.38
  5135.8 1942.48  5155.8 1941.86  5213.9 1942.55  5252.4 1941.70  5296.6 1942.00
  5332.2 1943.41  5354.7 1943.18  5390.5 1944.12  5429.0 1943.10  5467.4 1943.10
  5599.8 1943.40  5627.5 1944.01  5704.5 1943.49  5783.7 1944.34  5909.1 1944.24
#Mann=3,-1,0
  4546.5    0.05       0  4999.7    0.05       0  5003.7    0.05       0
Bank Sta=4999.7,5003.7
Exp/Cntr=0.3,0.1

Type RM Length L Ch R = 1,1041,104,104,104
BEGIN DESCRIPTION:
Elm 01 66 1041.1
END DESCRIPTION:
XS GIS Cut Line= 4
      1567195.15      6770743.62      1567537.14      6770622.10
      1567691.80      6770573.04      1568266.71      6770217.04
#Sta/Elev= 30
  4634.9 1948.45  4700.1 1946.76  4731.0 1946.70  4756.5 1944.69  4818.2 1942.55
  4843.8 1942.79  4905.5 1940.86  4961.9 1941.70  4992.7 1941.04  4994.5 1939.66
  4994.8 1939.16  4998.3 1939.16  4998.5 1939.66  5006.1 1941.12  5069.0 1941.77
  5094.7 1941.16  5180.3 1942.15  5232.3 1941.47  5281.5 1942.30  5399.1 1941.67
  5427.3 1942.15  5479.3 1941.35  5500.6 1941.49  5506.5 1942.08  5516.0 1940.76
  5537.2 1941.79  5610.5 1943.12  5653.0 1942.80  5668.4 1943.36  5836.3 1944.34
#Mann=3,-1,0
  4634.9    0.05       0  4994.5    0.05       0  4998.5    0.05       0
Bank Sta=4994.5,4998.5
Exp/Cntr=0.3,0.1

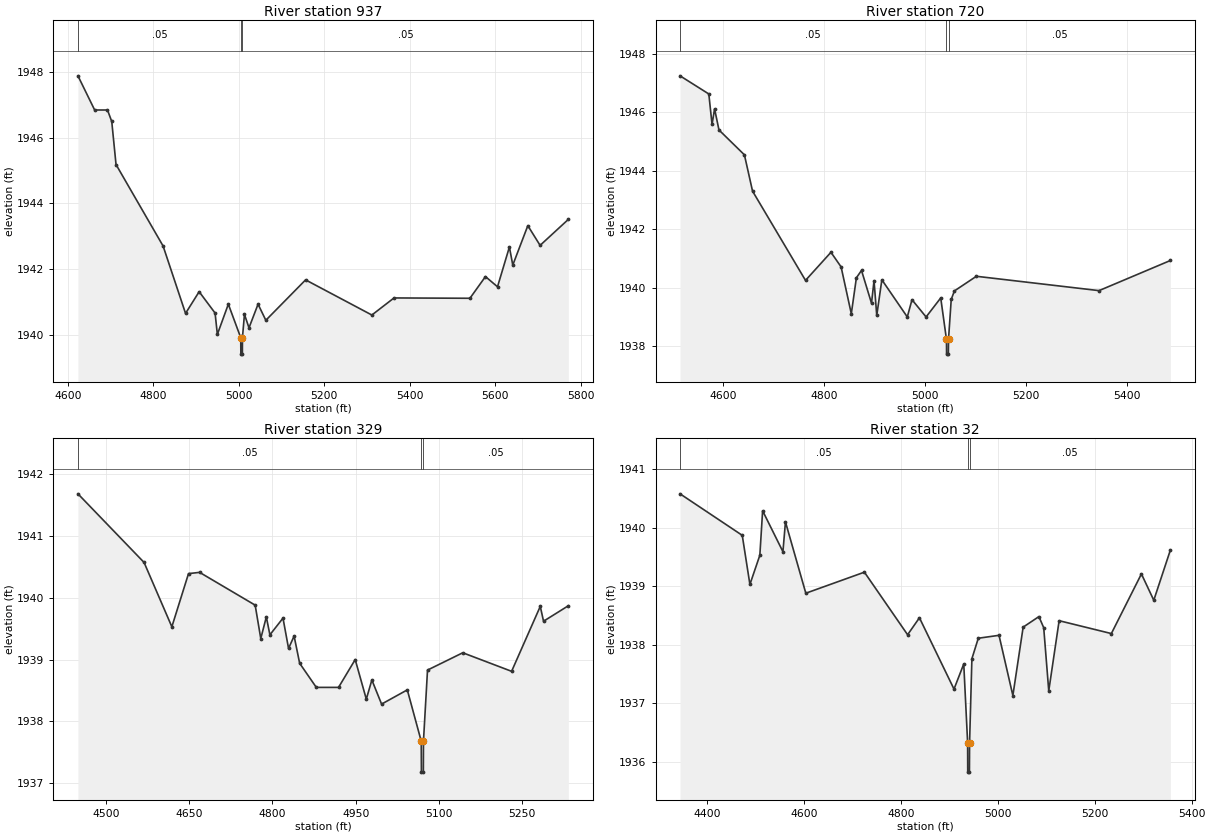
Type RM Length L Ch R = 1,937,217,217,217
BEGIN DESCRIPTION:
Mapping XS 4c64efec
END DESCRIPTION:
XS GIS Cut Line= 4
      1567245.91      6770756.09      1567452.50      6770750.88
      1567912.57      6770589.42      1568263.23      6770303.00
#Sta/Elev= 30
  4623.8 1947.88  4662.9 1946.84  4692.9 1946.84  4702.9 1946.49  4712.9 1945.18
  4823.0 1942.70  4875.5 1940.65  4907.3 1941.31  4944.6 1940.66  4949.9 1940.01
  4975.6 1940.93  5004.6 1939.91  5004.9 1939.41  5008.4 1939.41  5008.6 1939.91
  5013.3 1940.62  5023.9 1940.21  5045.1 1940.93  5063.3 1940.44  5156.3 1941.67
  5311.3 1940.60  5363.1 1941.12  5540.7 1941.11  5577.0 1941.77  5605.2 1941.46
  5633.0 1942.67  5640.9 1942.12  5676.1 1943.32  5704.8 1942.72  5770.8 1943.51
#Mann=3,-1,0
  4623.8    0.05       0  5004.6    0.05       0  5008.6    0.05       0
Bank Sta=5004.6,5008.6
Exp/Cntr=0.3,0.1

Type RM Length L Ch R = 1,720,391,391,391
BEGIN DESCRIPTION:
Elm 01 66 719.93
END DESCRIPTION:
XS GIS Cut Line= 3
      1567278.47      6770774.88      1567759.37      6770835.64
      1568144.77      6770538.78
#Sta/Elev= 30
  4515.3 1947.24  4572.3 1946.62  4578.7 1945.58  4583.7 1946.11  4592.4 1945.39
  4642.8 1944.54  4658.9 1943.30  4763.8 1940.25  4814.2 1941.21  4834.3 1940.71
  4854.5 1939.11  4864.6 1940.34  4874.7 1940.59  4894.5 1939.47  4899.5 1940.24
  4904.9 1939.05  4915.0 1940.27  4965.4 1939.00  4974.7 1939.59  5002.6 1939.00
  5031.6 1939.65  5043.0 1938.23  5043.2 1937.73  5046.7 1937.73  5047.0 1938.23
  5052.4 1939.60  5058.7 1939.89  5102.2 1940.39  5345.1 1939.90  5486.5 1940.93
#Mann=3,-1,0
  4515.3    0.05       0  5043.0    0.05       0  5047.0    0.05       0
Bank Sta=5043,5047
Exp/Cntr=0.3,0.1

Type RM Length L Ch R = 1,329,297,297,297
BEGIN DESCRIPTION:
Elm 01 66 329.32
END DESCRIPTION:
XS GIS Cut Line= 3
      1567525.94      6770944.91      1568074.91      6770957.71
      1568254.61      6770676.43
#Sta/Elev= 30
  4450.0 1941.68  4569.1 1940.57  4619.1 1939.53  4649.1 1940.39  4669.1 1940.41
  4769.1 1939.88  4779.2 1939.34  4789.2 1939.69  4795.6 1939.40  4819.2 1939.67
  4829.2 1939.18  4839.2 1939.38  4849.2 1938.94  4879.2 1938.55  4919.2 1938.55
  4949.2 1939.00  4969.2 1938.36  4979.2 1938.67  4996.7 1938.28  5043.0 1938.51
  5068.1 1937.68  5068.4 1937.18  5071.9 1937.18  5072.1 1937.68  5079.4 1938.83
  5142.9 1939.11  5230.8 1938.81  5282.4 1939.86  5288.3 1939.62  5332.9 1939.87
#Mann=3,-1,0
  4450.0    0.05       0  5068.1    0.03       0  5072.1    0.05       0
Bank Sta=5068.1,5072.1
Exp/Cntr=0.3,0.1

Type RM Length L Ch R = 1,32,0,0,0
BEGIN DESCRIPTION:
Elm 01 66 1388.129
END DESCRIPTION:
XS GIS Cut Line= 5
      1567614.93      6770973.12      1568139.00      6771098.99
      1568254.90      6771106.19      1568328.89      6771084.88
      1568421.70      6770821.55
#Sta/Elev= 30
  4344.9 1940.58  4473.2 1939.87  4489.0 1939.03  4509.5 1939.53  4515.2 1940.29
  4557.1 1939.59  4562.3 1940.10  4604.3 1938.88  4725.1 1939.24  4814.2 1938.17
  4838.6 1938.46  4909.9 1937.24  4930.0 1937.67  4938.0 1936.32  4938.2 1935.82
  4941.7 1935.82  4942.0 1936.32  4946.8 1937.76  4960.0 1938.11  5002.7 1938.16
  5031.3 1937.13  5052.5 1938.30  5085.0 1938.48  5094.9 1938.29  5105.3 1937.21
  5126.7 1938.41  5234.4 1938.19  5296.4 1939.21  5321.9 1938.76  5356.2 1939.62
#Mann=3,-1,0
  4344.9    0.05       0  4938.0    0.05       0  4942.0    0.05       0
Bank Sta=4938,4942
Exp/Cntr=0.3,0.1

Chan Stop Cuts=-1