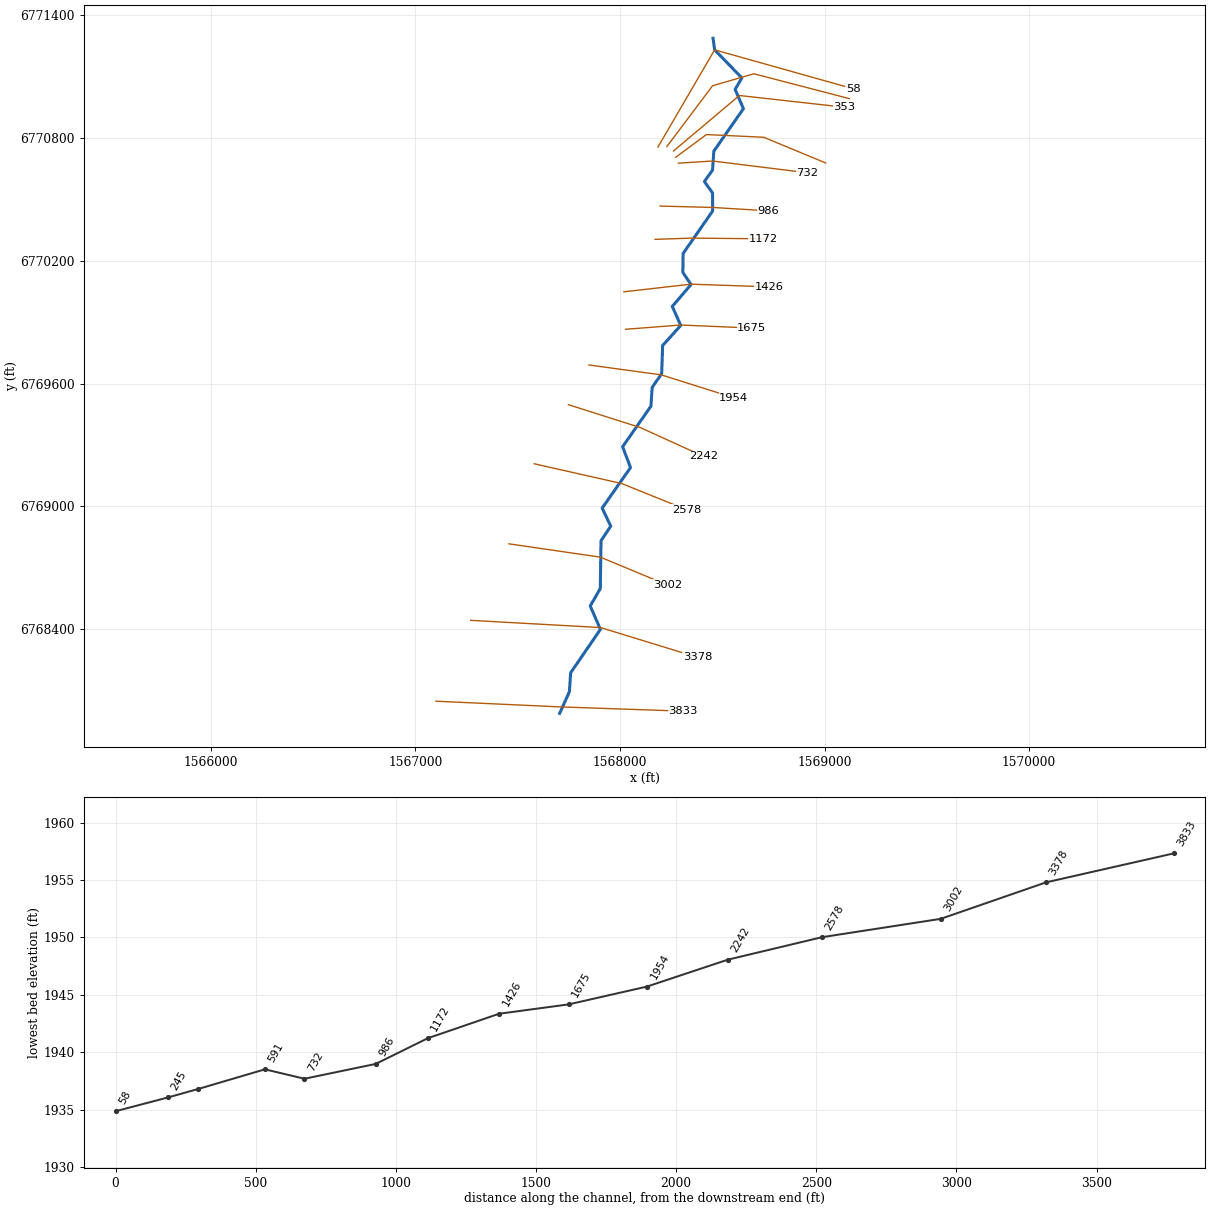
--- Elm 01 67.prj (project) ---

Proj Title=Elm 01 67 Base Level Engineering
Current Plan=p01
Default Exp/Contr=0.3,0.1
English Units
Geom File=g01
Flow File=f01
Plan File=p01
BEGIN DESCRIPTION:
Elm 01 67
END DESCRIPTION:

--- Elm 01 67.p01 (plan) ---

Plan Title=Multiple Run
Short Identifier=Multiple
Geom File=g01
Flow File=f01
Subcritical Flow
K Sum by GR= 0
Std Step Tol= 0.01
Critical Tol= 0.01
Num of Std Step Trials= 20
Max Error Tol= 0.3
Flow Tol Ratio= 0.001
Split Flow NTrial= 30
Split Flow Tol= 0.02
Split Flow Ratio= 0.02
Log Output Level= 0
Friction Slope Method= 1
Unsteady Friction Slope Method= 2
Unsteady Bridges Friction Slope Method= 1
Parabolic Critical Depth
Global Vel Dist=  1 , 1 , 1
Global Log Level= 0
CheckData=True
Encroach Param= -1, 0, 0, 0
BEGIN DESCRIPTION:
Multiple Run
END DESCRIPTION:

--- Elm 01 67.f01 (steady flow) ---

Flow Title=Multiple
Number of Profiles=7
Profile Names=10-year,25-year,50-year,1pct_min,100-year,1pct_plu,500-year
River Rch & RM= Elm 01 67,Reach-1,3833
      86     111     130      95     152     209     211
Boundary for River Rch & Prof#=Elm 01 67,Reach-1,1
Up Type=0
Dn Type=3
Dn Slope=0.001
Boundary for River Rch & Prof#=Elm 01 67,Reach-1,2
Up Type=0
Dn Type=3
Dn Slope=0.001
Boundary for River Rch & Prof#=Elm 01 67,Reach-1,3
Up Type=0
Dn Type=3
Dn Slope=0.001
Boundary for River Rch & Prof#=Elm 01 67,Reach-1,4
Up Type=0
Dn Type=3
Dn Slope=0.001
Boundary for River Rch & Prof#=Elm 01 67,Reach-1,5
Up Type=0
Dn Type=3
Dn Slope=0.001
Boundary for River Rch & Prof#=Elm 01 67,Reach-1,6
Up Type=0
Dn Type=3
Dn Slope=0.001
Boundary for River Rch & Prof#=Elm 01 67,Reach-1,7
Up Type=0
Dn Type=3
Dn Slope=0.001

--- Elm 01 67.g01 (geometry) ---

Geom Title=Existing Conditions

River Reach=Elm 01 67,Reach-1
Reach XY= 30
      1567705.00      6767988.00      1567752.77      6768093.92
      1567758.82      6768186.42      1567904.39      6768398.63
      1567854.61      6768513.00      1567903.76      6768598.50
      1567907.29      6768832.07      1567954.85      6768903.42
      1567912.83      6768991.40      1568051.63      6769189.74
      1568012.83      6769291.40      1568151.17      6769489.58
      1568157.36      6769582.02      1568203.77      6769648.51
      1568208.57      6769786.53      1568297.16      6769884.60
      1568255.66      6769977.36      1568347.19      6770084.59
      1568307.37      6770143.89      1568308.68      6770236.41
      1568453.02      6770443.90      1568452.64      6770532.10
      1568412.56      6770588.00      1568452.45      6770643.89
      1568458.82      6770736.41      1568603.34      6770944.05
      1568562.84      6771038.09      1568595.71      6771094.67
      1568462.76      6771231.79      1568455.00      6771288.00

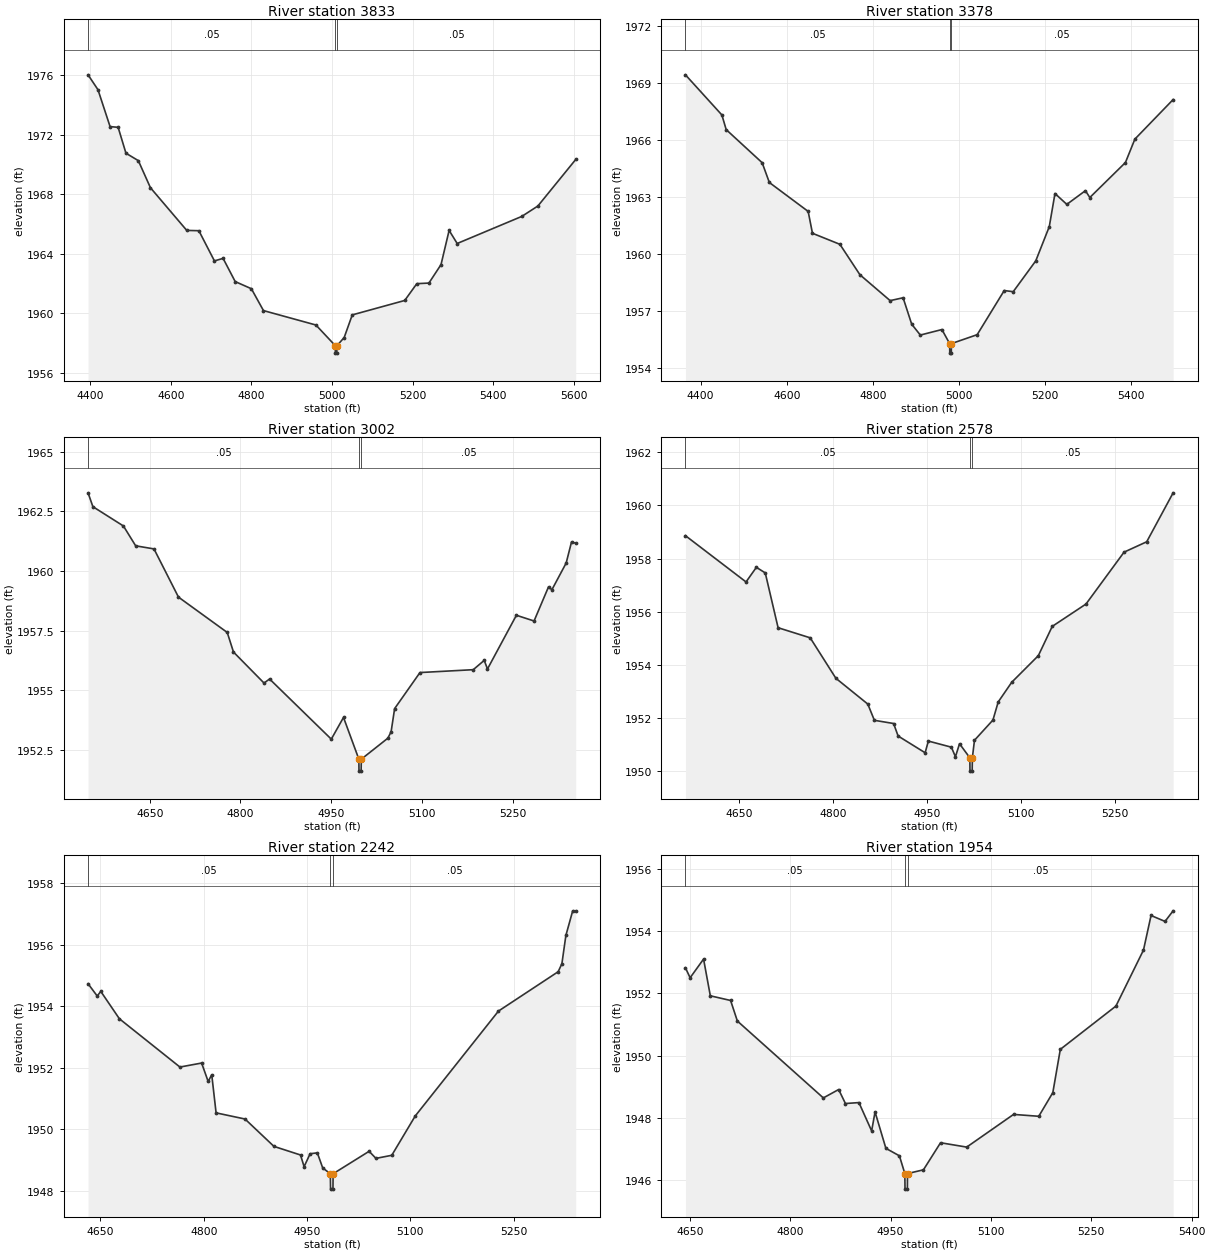
Type RM Length L Ch R = 1,3833,455,455,455
BEGIN DESCRIPTION:
Elm 01 67 3414.111
END DESCRIPTION:
XS GIS Cut Line= 3
      1567100.45      6768047.51      1567705.12      6768019.80
      1568308.86      6767998.89
#Sta/Elev= 30
  4394.7 1976.02  4419.3 1975.02  4449.3 1972.54  4469.3 1972.49  4488.7 1970.75
  4519.4 1970.25  4549.4 1968.43  4639.5 1965.56  4669.5 1965.54  4708.1 1963.51
  4729.6 1963.68  4759.6 1962.12  4799.7 1961.64  4829.7 1960.17  4959.8 1959.20
  5007.9 1957.81  5008.1 1957.31  5011.6 1957.31  5011.9 1957.81  5029.9 1958.36
  5049.9 1959.88  5180.0 1960.85  5210.0 1961.98  5240.0 1962.02  5270.0 1963.26
  5290.1 1965.56  5310.1 1964.68  5470.2 1966.50  5510.2 1967.20  5604.1 1970.33
#Mann=3,-1,0
  4394.7    0.05       0  5007.9    0.05       0  5011.9    0.05       0
Bank Sta=5007.9,5011.9
Exp/Cntr=0.3,0.1

Type RM Length L Ch R = 1,3378,376,376,376
BEGIN DESCRIPTION:
Elm 01 67 3377.94
END DESCRIPTION:
XS GIS Cut Line= 3
      1567270.52      6768442.77      1567904.63      6768407.61
      1568379.87      6768261.78
#Sta/Elev= 30
  4364.7 1969.42  4449.3 1967.31  4459.3 1966.54  4542.8 1964.80  4559.5 1963.76
  4649.6 1962.24  4659.6 1961.09  4723.3 1960.51  4769.8 1958.91  4839.9 1957.55
  4870.0 1957.70  4890.0 1956.31  4910.0 1955.74  4960.1 1956.03  4978.1 1955.29
  4978.4 1954.79  4981.9 1954.79  4982.1 1955.29  5042.0 1955.76  5104.8 1958.08
  5125.7 1958.02  5178.0 1959.64  5209.4 1961.44  5222.6 1963.18  5250.1 1962.61
  5293.3 1963.33  5303.5 1962.97  5386.2 1964.81  5408.1 1966.04  5496.9 1968.12
#Mann=3,-1,0
  4364.7    0.05       0  4978.1    0.05       0  4982.1    0.05       0
Bank Sta=4978.1,4982.1
Exp/Cntr=0.3,0.1

Type RM Length L Ch R = 1,3002,424,424,424
BEGIN DESCRIPTION:
Elm 01 67 3002.28
END DESCRIPTION:
XS GIS Cut Line= 3
      1567457.11      6768816.85      1567904.14      6768751.74
      1568231.42      6768615.65
#Sta/Elev= 30
  4548.0 1963.27  4556.0 1962.69  4606.5 1961.88  4626.7 1961.05  4657.0 1960.92
  4697.5 1958.90  4778.1 1957.42  4788.4 1956.60  4838.9 1955.30  4848.1 1955.47
  4950.1 1952.95  4970.3 1953.86  4995.7 1952.11  4995.9 1951.61  4999.4 1951.61
  4999.7 1952.11  5043.6 1952.99  5049.0 1953.26  5054.8 1954.23  5096.7 1955.74
  5184.8 1955.86  5202.9 1956.25  5208.3 1955.89  5256.1 1958.14  5285.3 1957.90
  5309.2 1959.33  5314.8 1959.21  5338.4 1960.33  5347.2 1961.21  5354.2 1961.16
#Mann=3,-1,0
  4548.0    0.05       0  4995.7    0.05       0  4999.7    0.05       0
Bank Sta=4995.7,4999.7
Exp/Cntr=0.3,0.1

Type RM Length L Ch R = 1,2578,336,336,336
BEGIN DESCRIPTION:
Elm 01 67 2577.75
END DESCRIPTION:
XS GIS Cut Line= 3
      1567580.61      6769208.21      1568007.66      6769111.86
      1568324.11      6768984.24
#Sta/Elev= 30
  4564.0 1958.86  4660.8 1957.12  4677.3 1957.67  4691.5 1957.46  4712.0 1955.40
  4763.3 1955.02  4804.3 1953.50  4855.3 1952.53  4865.8 1951.92  4896.5 1951.80
  4903.7 1951.33  4946.9 1950.70  4952.0 1951.14  4988.8 1950.91  4995.3 1950.55
  5001.8 1951.04  5018.3 1950.51  5018.5 1950.01  5022.0 1950.01  5022.3 1950.51
  5025.7 1951.17  5055.2 1951.93  5063.6 1952.61  5085.2 1953.35  5127.7 1954.35
  5149.9 1955.45  5203.8 1956.29  5264.6 1958.24  5300.8 1958.63  5343.0 1960.47
#Mann=3,-1,0
  4564.0    0.05       0  5018.3    0.05       0  5022.3    0.05       0
Bank Sta=5018.3,5022.3
Exp/Cntr=0.3,0.1

Type RM Length L Ch R = 1,2242,288,288,288
BEGIN DESCRIPTION:
Elm 01 67 2242.22
END DESCRIPTION:
XS GIS Cut Line= 3
      1567747.84      6769497.18      1568099.45      6769385.19
      1568408.01      6769244.58
#Sta/Elev= 30
  4632.0 1954.73  4645.3 1954.33  4650.5 1954.48  4677.5 1953.59  4765.4 1952.02
  4796.9 1952.15  4806.4 1951.55  4811.6 1951.77  4817.9 1950.53  4859.9 1950.33
  4901.9 1949.44  4940.5 1949.16  4945.7 1948.78  4954.4 1949.20  4964.9 1949.23
  4972.7 1948.74  4983.8 1948.55  4984.1 1948.05  4987.6 1948.05  4987.8 1948.55
  5040.1 1949.28  5050.0 1949.05  5073.0 1949.15  5107.1 1950.43  5227.9 1953.84
  5314.6 1955.12  5320.0 1955.38  5325.8 1956.30  5335.7 1957.10  5340.1 1957.10
#Mann=3,-1,0
  4632.0    0.05       0  4983.8    0.05       0  4987.8    0.05       0
Bank Sta=4983.8,4987.8
Exp/Cntr=0.3,0.1

Type RM Length L Ch R = 1,1954,279,279,279
BEGIN DESCRIPTION:
Elm 01 67 1953.57
END DESCRIPTION:
XS GIS Cut Line= 3
      1567848.11      6769691.18      1568201.02      6769643.00
      1568556.52      6769531.01
#Sta/Elev= 30
  4643.4 1952.82  4650.4 1952.50  4670.5 1953.10  4680.6 1951.92  4710.9 1951.77
  4721.0 1951.11  4849.5 1948.64  4872.4 1948.91  4882.5 1948.46  4902.7 1948.49
  4921.7 1947.58  4926.8 1948.19  4943.0 1947.02  4963.2 1946.78  4971.3 1946.21
  4971.6 1945.71  4975.1 1945.71  4975.3 1946.21  4999.1 1946.33  5024.7 1947.20
  5063.8 1947.06  5133.8 1948.11  5171.5 1948.05  5192.5 1948.81  5203.7 1950.20
  5286.8 1951.59  5328.0 1953.39  5339.3 1954.50  5360.2 1954.31  5372.3 1954.65
#Mann=3,-1,0
  4643.4    0.05       0  4971.3    0.05       0  4975.3    0.05       0
Bank Sta=4971.3,4975.3
Exp/Cntr=0.3,0.1

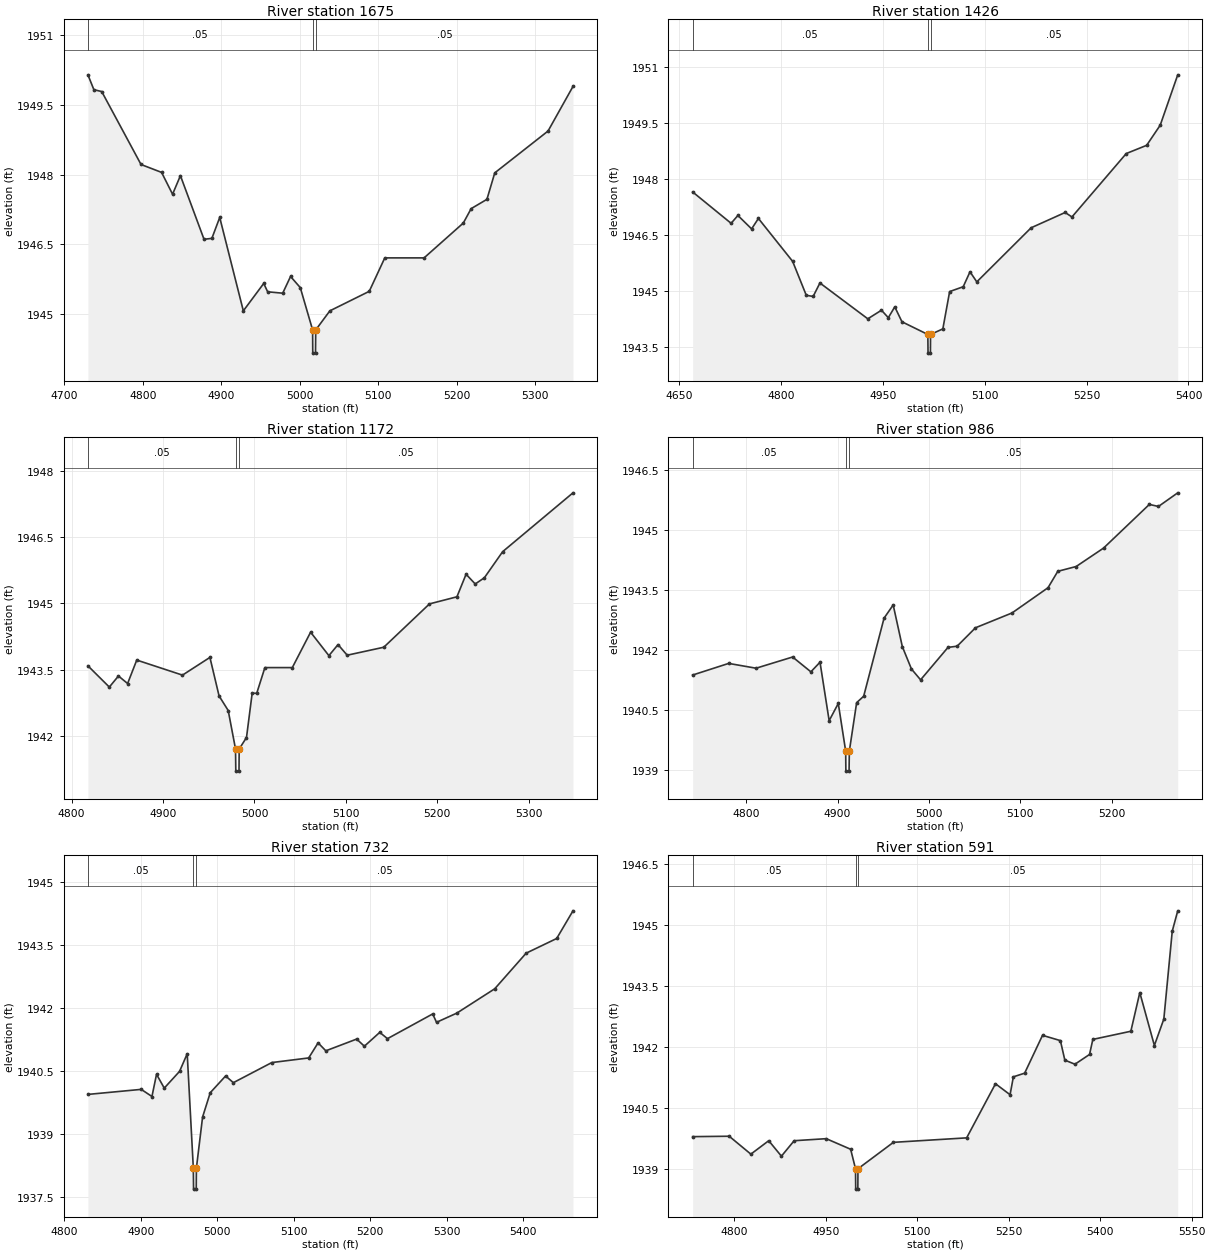
Type RM Length L Ch R = 1,1675,249,249,249
BEGIN DESCRIPTION:
Elm 01 67 1674.55
END DESCRIPTION:
XS GIS Cut Line= 3
      1568027.46      6769865.69      1568297.41      6769886.53
      1568644.65      6769871.77
#Sta/Elev= 30
  4730.0 1950.15  4737.6 1949.83  4747.6 1949.79  4797.7 1948.22  4823.9 1948.05
  4837.9 1947.58  4847.9 1947.98  4878.0 1946.61  4888.0 1946.63  4898.0 1947.08
  4928.1 1945.07  4954.1 1945.66  4959.1 1945.48  4978.3 1945.45  4988.3 1945.81
  5000.7 1945.57  5016.4 1944.66  5016.6 1944.16  5020.1 1944.16  5020.4 1944.66
  5038.4 1945.07  5088.6 1945.49  5108.4 1946.21  5158.5 1946.21  5208.5 1946.96
  5218.5 1947.27  5238.6 1947.47  5248.6 1948.04  5316.5 1948.94  5348.3 1949.90
#Mann=3,-1,0
  4730.0    0.05       0  5016.4    0.03       0  5020.4    0.05       0
Bank Sta=5016.4,5020.4
Exp/Cntr=0.3,0.1

Type RM Length L Ch R = 1,1426,254,254,254
BEGIN DESCRIPTION:
Elm 01 67 1426.09
END DESCRIPTION:
XS GIS Cut Line= 3
      1568018.78      6770048.86      1568346.89      6770086.18
      1568730.75      6770073.18
#Sta/Elev= 30
  4669.9 1947.66  4726.5 1946.82  4736.5 1947.03  4756.7 1946.67  4766.7 1946.95
  4817.1 1945.80  4837.2 1944.89  4847.3 1944.86  4857.3 1945.22  4927.8 1944.26
  4947.9 1944.49  4958.0 1944.29  4967.5 1944.58  4978.1 1944.18  5016.2 1943.84
  5016.5 1943.34  5020.0 1943.34  5020.2 1943.84  5038.3 1943.99  5048.3 1944.99
  5068.3 1945.12  5078.3 1945.52  5088.3 1945.25  5168.3 1946.70  5218.4 1947.11
  5228.4 1946.99  5308.4 1948.69  5338.4 1948.91  5358.4 1949.45  5384.2 1950.80
#Mann=3,-1,0
  4669.9    0.05       0  5016.2    0.03       0  5020.2    0.05       0
Bank Sta=5016.2,5020.2
Exp/Cntr=0.3,0.1

Type RM Length L Ch R = 1,1172,186,186,186
BEGIN DESCRIPTION:
Elm 01 67 1172.48
END DESCRIPTION:
XS GIS Cut Line= 3
      1568171.65      6770305.33      1568352.21      6770311.41
      1568701.93      6770307.96
#Sta/Elev= 30
  4817.9 1943.59  4841.3 1943.11  4851.3 1943.36  4861.3 1943.19  4871.3 1943.72
  4921.3 1943.38  4951.3 1943.78  4961.3 1942.91  4971.3 1942.58  4979.3 1941.71
  4979.6 1941.21  4983.1 1941.21  4983.3 1941.71  4991.3 1941.97  4997.5 1942.97
  5002.5 1942.97  5011.4 1943.55  5041.4 1943.55  5061.4 1944.35  5081.4 1943.82
  5091.4 1944.07  5101.4 1943.83  5141.4 1944.01  5191.4 1944.99  5221.4 1945.15
  5231.4 1945.66  5241.4 1945.44  5251.4 1945.58  5271.4 1946.17  5348.3 1947.50
#Mann=3,-1,0
  4817.9    0.05       0  4979.3    0.03       0  4983.3    0.05       0
Bank Sta=4979.3,4983.3
Exp/Cntr=0.3,0.1

Type RM Length L Ch R = 1,986,254,254,254
BEGIN DESCRIPTION:
Elm 01 67 986.14
END DESCRIPTION:
XS GIS Cut Line= 3
      1568195.61      6770468.10      1568454.29      6770461.15
      1568726.02      6770444.66
#Sta/Elev= 30
  4741.4 1941.37  4780.8 1941.66  4810.8 1941.54  4850.8 1941.82  4870.8 1941.45
  4880.8 1941.69  4890.8 1940.23  4900.8 1940.66  4908.9 1939.47  4909.1 1938.97
  4912.6 1938.97  4912.9 1939.47  4920.9 1940.68  4928.6 1940.84  4950.9 1942.79
  4960.9 1943.12  4970.9 1942.08  4980.9 1941.52  4990.9 1941.25  5020.9 1942.06
  5030.9 1942.09  5051.0 1942.55  5091.0 1942.92  5130.4 1943.55  5141.1 1943.96
  5161.2 1944.08  5191.2 1944.54  5241.3 1945.63  5251.3 1945.58  5272.4 1945.92
#Mann=3,-1,0
  4741.4    0.05       0  4908.9    0.03       0  4912.9    0.05       0
Bank Sta=4908.9,4912.9
Exp/Cntr=0.3,0.1

Type RM Length L Ch R = 1,732,141,141,141
BEGIN DESCRIPTION:
Elm 01 67 732.05
END DESCRIPTION:
XS GIS Cut Line= 3
      1568285.44      6770677.84      1568452.10      6770688.26
      1568915.69      6770630.96
#Sta/Elev= 30
  4831.0 1939.94  4900.7 1940.06  4914.7 1939.89  4920.7 1940.42  4930.8 1940.09
  4950.8 1940.49  4960.8 1940.91  4968.8 1938.18  4969.1 1937.68  4972.6 1937.68
  4972.8 1938.18  4980.9 1939.40  4990.9 1939.98  5011.0 1940.38  5021.1 1940.22
  5071.4 1940.70  5119.6 1940.81  5131.9 1941.17  5142.0 1940.98  5182.3 1941.26
  5192.4 1941.09  5212.5 1941.42  5222.6 1941.27  5281.7 1941.86  5286.7 1941.66
  5313.3 1941.88  5362.8 1942.46  5403.9 1943.31  5443.8 1943.66  5465.1 1944.32
#Mann=3,-1,0
  4831.0    0.05       0  4968.8    0.05       0  4972.8    0.05       0
Bank Sta=4968.8,4972.8
Exp/Cntr=0.3,0.1

Type RM Length L Ch R = 1,591,238,238,238
BEGIN DESCRIPTION:
Mapping XS 8c4c7ed9
END DESCRIPTION:
XS GIS Cut Line= 4
      1568272.54      6770706.84      1568422.28      6770817.52
      1568702.23      6770804.50      1569006.03      6770678.64
#Sta/Elev= 30
  4731.9 1939.79  4791.8 1939.80  4827.3 1939.36  4856.6 1939.69  4877.4 1939.31
  4898.3 1939.69  4950.9 1939.74  4990.9 1939.48  4998.9 1939.00  4999.2 1938.50
  5002.7 1938.50  5002.9 1939.00  5061.0 1939.65  5181.1 1939.76  5228.4 1941.09
  5252.3 1940.82  5257.7 1941.26  5276.2 1941.35  5305.5 1942.28  5334.8 1942.15
  5342.1 1941.67  5358.7 1941.57  5382.6 1941.81  5388.0 1942.18  5450.3 1942.38
  5465.0 1943.33  5488.9 1942.03  5504.4 1942.68  5518.2 1944.84  5527.2 1945.34
#Mann=3,-1,0
  4731.9    0.05       0  4998.9    0.03       0  5002.9    0.05       0
Bank Sta=4998.9,5002.9
Exp/Cntr=0.3,0.1

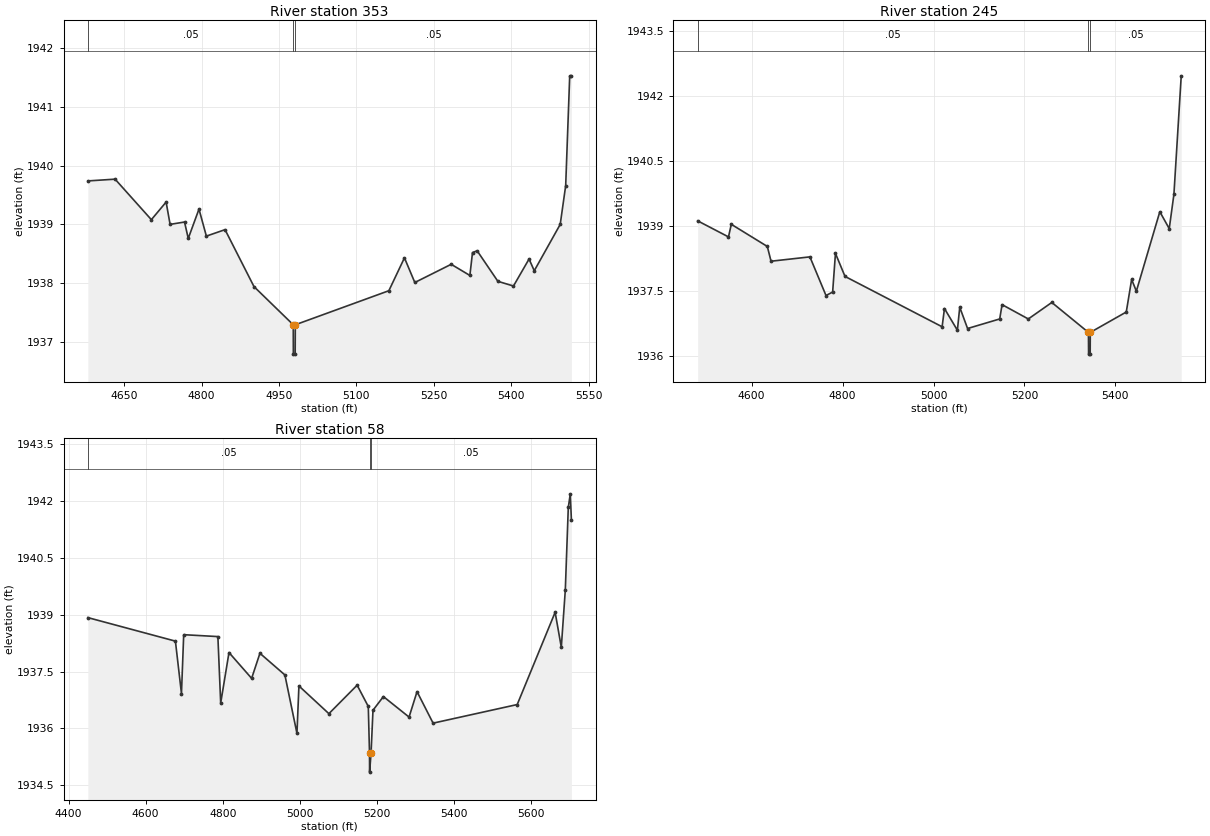
Type RM Length L Ch R = 1,353,108,108,108
BEGIN DESCRIPTION:
Elm 01 67 353.2
END DESCRIPTION:
XS GIS Cut Line= 3
      1568261.68      6770737.22      1568583.61      6771008.57
      1569096.59      6770951.28
#Sta/Elev= 30
  4579.6 1939.74  4632.4 1939.77  4702.7 1939.08  4731.3 1939.38  4739.0 1939.00
  4767.0 1939.04  4774.2 1938.76  4795.0 1939.26  4809.3 1938.80  4845.5 1938.91
  4901.6 1937.94  4977.7 1937.29  4977.9 1936.79  4981.4 1936.79  4981.7 1937.29
  5163.0 1937.87  5193.2 1938.43  5213.3 1938.01  5283.8 1938.32  5320.0 1938.13
  5325.1 1938.52  5334.1 1938.55  5374.3 1938.03  5404.5 1937.95  5434.7 1938.41
  5444.8 1938.21  5495.1 1939.00  5505.7 1939.66  5513.5 1941.53  5516.8 1941.53
#Mann=3,-1,0
  4579.6    0.05       0  4977.7    0.05       0  4981.7    0.05       0
Bank Sta=4977.7,4981.7
Exp/Cntr=0.3,0.1

Type RM Length L Ch R = 1,245,187,187,187
BEGIN DESCRIPTION:
Mapping XS a6de8905
END DESCRIPTION:
XS GIS Cut Line= 4
      1568229.16      6770758.96      1568452.66      6771056.24
      1568654.48      6771114.83      1569120.55      6770993.44
#Sta/Elev= 30
  4481.2 1939.12  4549.0 1938.75  4555.2 1939.04  4634.4 1938.53  4642.6 1938.19
  4728.1 1938.29  4763.5 1937.40  4778.1 1937.48  4784.3 1938.37  4805.3 1937.84
  5018.9 1936.68  5024.1 1937.10  5052.5 1936.60  5057.7 1937.13  5074.9 1936.64
  5145.6 1936.86  5150.8 1937.19  5208.5 1936.86  5260.2 1937.24  5340.8 1936.55
  5341.1 1936.05  5344.6 1936.05  5344.8 1936.55  5424.0 1937.02  5435.8 1937.77
  5446.2 1937.50  5497.8 1939.33  5518.5 1938.94  5528.8 1939.73  5544.9 1942.46
#Mann=3,-1,0
  4481.2    0.05       0  5340.8    0.05       0  5344.8    0.05       0
Bank Sta=5340.8,5344.8
Exp/Cntr=0.3,0.1

Type RM Length L Ch R = 1,58,0,0,0
BEGIN DESCRIPTION:
Elm 01 67 1947.464
END DESCRIPTION:
XS GIS Cut Line= 3
      1568185.74      6770756.76      1568462.76      6771231.79
      1569140.25      6771041.50
#Sta/Elev= 30
  4450.1 1938.92  4677.1 1938.30  4692.8 1936.92  4698.6 1938.47  4787.2 1938.42
  4794.5 1936.67  4816.0 1938.00  4874.7 1937.32  4896.2 1937.98  4960.9 1937.41
  4992.2 1935.87  4997.3 1937.12  5075.0 1936.39  5148.2 1937.14  5177.1 1936.58
  5180.3 1935.35  5180.5 1934.85  5184.3 1935.35  5189.3 1936.48  5216.3 1936.84
  5282.8 1936.30  5303.5 1936.97  5345.1 1936.14  5563.2 1936.63  5661.5 1939.06
  5677.5 1938.14  5687.9 1939.65  5695.6 1941.82  5700.8 1942.18  5703.7 1941.48
#Mann=3,-1,0
  4450.1    0.05       0  5180.3    0.03       0  5184.3    0.05       0
Bank Sta=5180.3,5184.3
Exp/Cntr=0.3,0.1

Chan Stop Cuts=-1