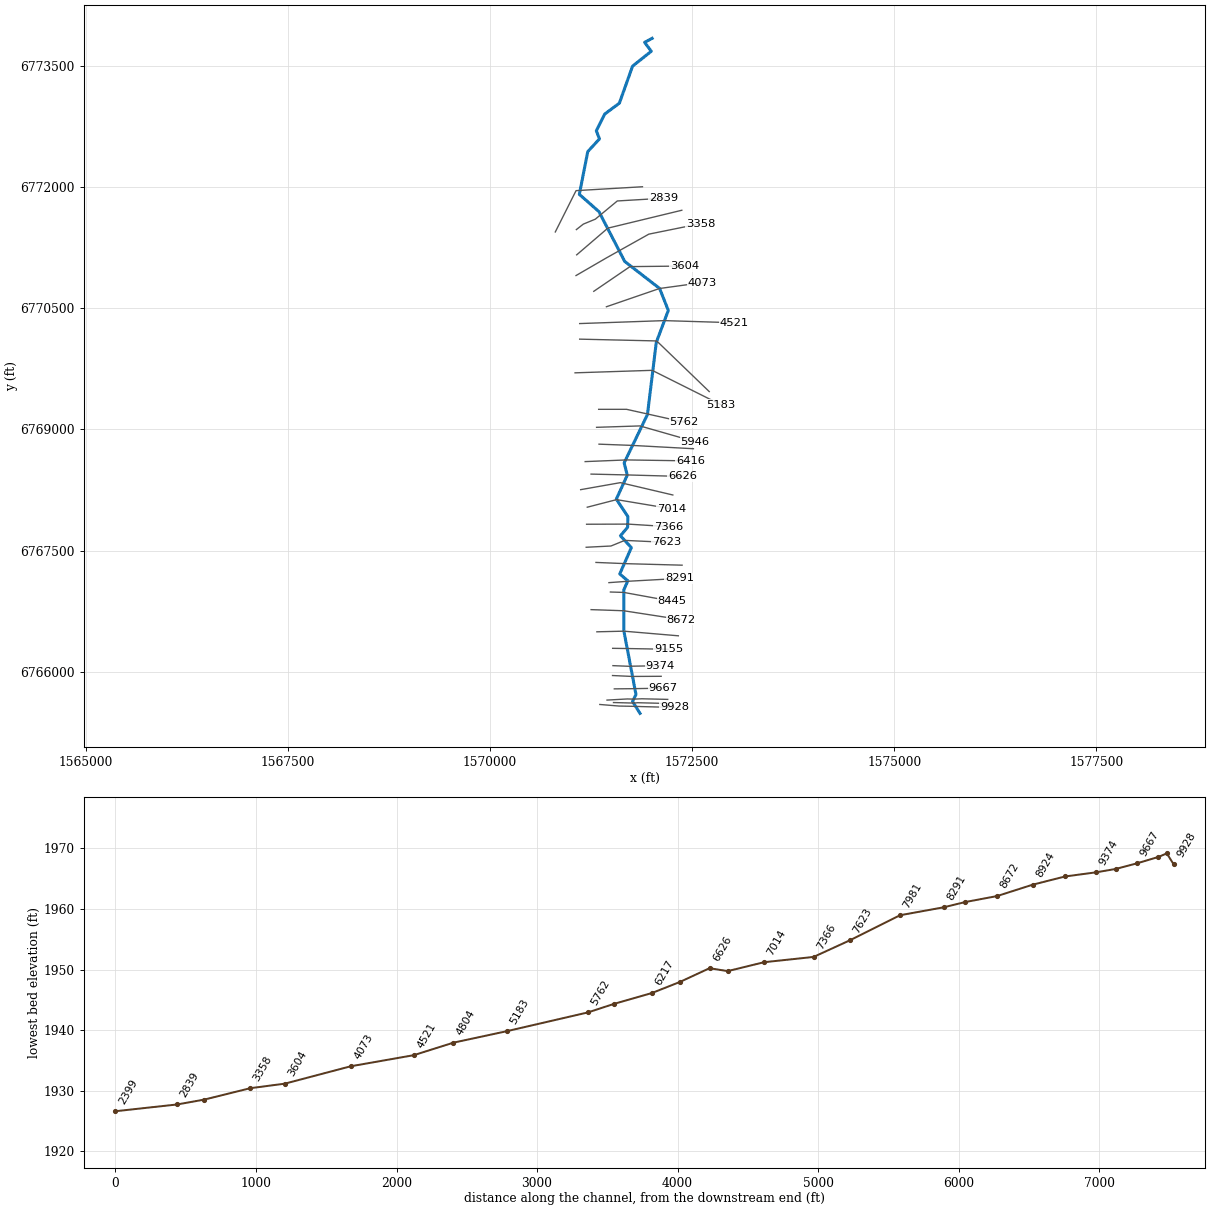
--- Elm 01 68.prj (project) ---

Proj Title=Elm 01 68 Base Level Engineering
Current Plan=p01
Default Exp/Contr=0.3,0.1
English Units
Geom File=g01
Flow File=f01
Plan File=p01
Y Axis Title=Elevation
X Axis Title(PF)=Main Channel Distance
X Axis Title(XS)=Station
BEGIN DESCRIPTION:
Elm 01 68
END DESCRIPTION:
DSS Export Rating Curves= 0
DSS Export Rating Curve Sorted= 0
DSS Export Volume Flow Curves= 0
DXF OffsetX= 0
DXF OffsetY= 0
DXF ScaleX= 1
DXF ScaleY= 10

--- Elm 01 68.p01 (plan) ---

Plan Title=Multiple Run
Short Identifier=Multiple
Geom File=g01
Flow File=f01
Subcritical Flow
K Sum by GR= 0
Std Step Tol= 0.01
Critical Tol= 0.01
Num of Std Step Trials= 20
Max Error Tol= 0.3
Flow Tol Ratio= 0.001
Split Flow NTrial= 30
Split Flow Tol= 0.02
Split Flow Ratio= 0.02
Log Output Level= 0
Friction Slope Method= 1
Unsteady Friction Slope Method= 2
Unsteady Bridges Friction Slope Method= 1
Parabolic Critical Depth
Global Vel Dist=  1 , 1 , 1
Global Log Level= 0
CheckData=True
Encroach Param= -1, 0, 0, 0
BEGIN DESCRIPTION:
Multiple Run
END DESCRIPTION:

--- Elm 01 68.f01 (steady flow) ---

Flow Title=Multiple
Program Version=4.10
Number of Profiles= 7
Profile Names=10-year,25-year,50-year,1pct_min,100-year,1pct_plu,500-year
River Rch & RM=Elm 01 68,Reach-1         ,9928
     105     137     163     120     192     264     270
River Rch & RM=Elm 01 68,Reach-1         ,5183
     163     219     264     197     316     435     459
River Rch & RM=Elm 01 68,Reach-1         ,4073
     163     219     264     197     316     435     459
Boundary for River Rch & Prof#=Elm 01 68,Reach-1         , 1
Up Type= 0
Dn Type= 3
Dn Slope=0.001
Boundary for River Rch & Prof#=Elm 01 68,Reach-1         , 2
Up Type= 0
Dn Type= 3
Dn Slope=0.001
Boundary for River Rch & Prof#=Elm 01 68,Reach-1         , 3
Up Type= 0
Dn Type= 3
Dn Slope=0.001
Boundary for River Rch & Prof#=Elm 01 68,Reach-1         , 4
Up Type= 0
Dn Type= 3
Dn Slope=0.001
Boundary for River Rch & Prof#=Elm 01 68,Reach-1         , 5
Up Type= 0
Dn Type= 3
Dn Slope=0.001
Boundary for River Rch & Prof#=Elm 01 68,Reach-1         , 6
Up Type= 0
Dn Type= 3
Dn Slope=0.001
Boundary for River Rch & Prof#=Elm 01 68,Reach-1         , 7
Up Type= 0
Dn Type= 3
Dn Slope=0.001
DSS Import GetInterval= 0
DSS Import GetPeak= 0
DSS Import FillOption= 0

--- Elm 01 68.g01 (geometry) ---

Geom Title=Existing Conditions

River Reach=Elm 01 68,Reach-1
Reach XY= 30
      1571855.00      6765488.00      1571763.05      6765634.69
      1571804.85      6765722.58      1571655.07      6766508.03
      1571655.09      6767017.98      1571704.44      6767127.52
      1571604.39      6767212.92      1571747.71      6767538.09
      1571612.60      6767684.66      1571701.45      6767789.47
      1571704.51      6767922.78      1571562.10      6768138.00
      1571697.17      6768434.58      1571658.68      6768586.41
      1571946.99      6769184.67      1572056.22      6770077.50
      1572204.93      6770472.61      1572097.27      6770744.24
      1571665.76      6771078.32      1571346.98      6771694.34
      1571104.61      6771908.13      1571208.54      6772436.53
      1571353.34      6772594.05      1571314.43      6772694.61
      1571418.47      6772901.57      1571599.48      6773035.56
      1571762.86      6773494.17      1571994.17      6773677.68
      1571911.84      6773788.16      1572005.00      6773838.00

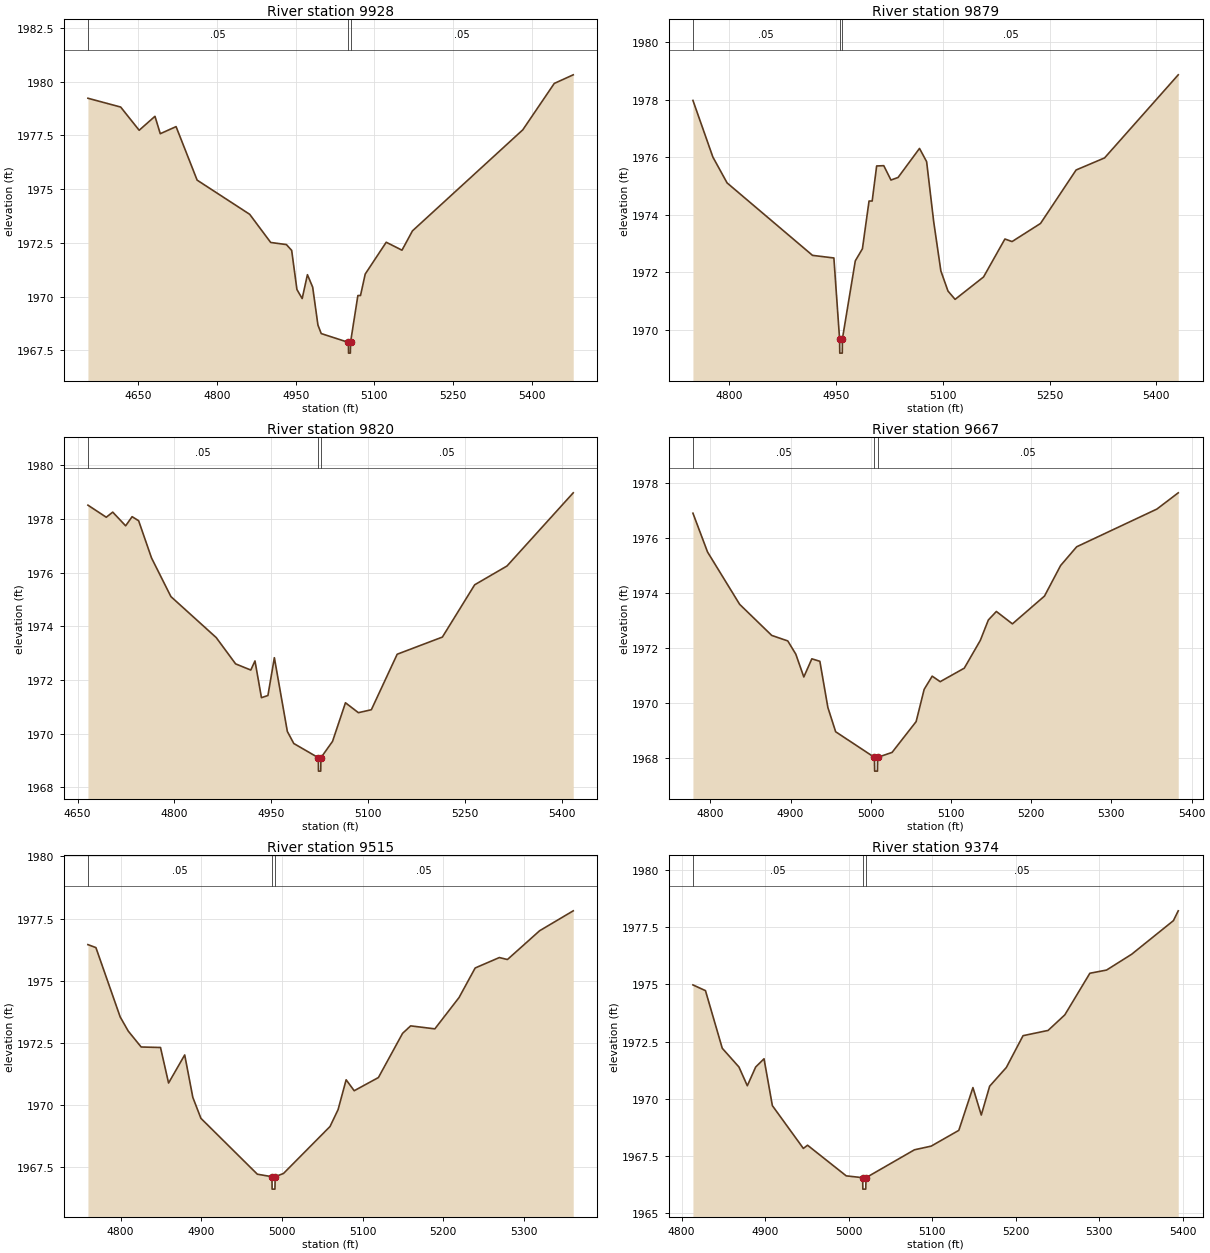
Type RM Length L Ch R = 1,9928,49,49,49
BEGIN DESCRIPTION:
Elm 01 68 9854.646
END DESCRIPTION:
XS GIS Cut Line= 5
      1571357.71      6765598.08      1571596.45      6765578.55
      1571802.57      6765574.55      1571872.05      6765572.04
      1572281.08      6765561.21
#Sta/Elev= 30
  4554.3 1979.23  4616.7 1978.82  4651.9 1977.74  4682.0 1978.39  4692.1 1977.58
  4722.2 1977.91  4762.3 1975.42  4862.4 1973.83  4902.4 1972.52  4932.4 1972.42
  4942.4 1972.15  4952.4 1970.33  4962.4 1969.91  4972.4 1971.02  4982.4 1970.44
  4992.4 1968.68  4998.7 1968.28  5050.5 1967.87  5050.7 1967.37  5054.2 1967.37
  5054.5 1967.87  5068.5 1970.05  5073.5 1970.05  5082.5 1971.05  5122.5 1972.53
  5152.5 1972.16  5172.5 1973.06  5382.6 1977.76  5442.6 1979.92  5478.7 1980.32
#Mann=3,-1,0
  4554.3    0.05       0  5050.5    0.03       0  5054.5    0.05       0
Bank Sta=5050.5,5054.5
Exp/Cntr=0.3,0.1

Type RM Length L Ch R = 1,9879,59,59,59
BEGIN DESCRIPTION:
Elm 01 68 9879.04
END DESCRIPTION:
XS GIS Cut Line= 4
      1571527.02      6765621.95      1571778.74      6765615.44
      1571827.57      6765619.78      1572208.42      6765610.01
#Sta/Elev= 30
  4748.9 1977.97  4776.9 1976.00  4796.9 1975.10  4916.9 1972.58  4946.9 1972.49
  4954.9 1969.68  4955.2 1969.18  4958.7 1969.18  4958.9 1969.68  4977.0 1972.39
  4987.0 1972.81  4996.3 1974.47  5000.7 1974.47  5007.0 1975.69  5017.0 1975.70
  5027.1 1975.20  5037.1 1975.29  5067.2 1976.30  5077.2 1975.84  5087.2 1973.74
  5097.2 1972.04  5107.2 1971.34  5117.2 1971.05  5157.2 1971.83  5187.2 1973.15
  5197.2 1973.06  5237.2 1973.69  5287.2 1975.55  5327.2 1975.97  5430.7 1978.86
#Mann=3,-1,0
  4748.9    0.05       0  4954.9    0.05       0  4958.9    0.05       0
Bank Sta=4954.9,4958.9
Exp/Cntr=0.3,0.1

Type RM Length L Ch R = 1,9820,153,153,153
BEGIN DESCRIPTION:
Elm 01 68 9819.58
END DESCRIPTION:
XS GIS Cut Line= 5
      1571446.66      6765652.33      1571698.44      6765666.44
      1571778.74      6765664.27      1571877.48      6765668.61
      1572197.55      6765661.01
#Sta/Elev= 30
  4666.0 1978.52  4694.4 1978.07  4704.4 1978.26  4724.4 1977.75  4734.4 1978.09
  4744.5 1977.94  4764.5 1976.55  4794.5 1975.11  4864.7 1973.58  4894.7 1972.60
  4918.2 1972.37  4924.7 1972.71  4934.7 1971.34  4944.7 1971.42  4954.7 1972.83
  4974.8 1970.08  4984.8 1969.63  5022.8 1969.10  5023.0 1968.60  5026.5 1968.60
  5026.8 1969.10  5044.8 1969.71  5064.8 1971.15  5084.8 1970.78  5104.9 1970.89
  5144.9 1972.96  5214.9 1973.60  5264.9 1975.55  5314.9 1976.25  5417.5 1978.98
#Mann=3,-1,0
  4666.0    0.05       0  5022.8    0.05       0  5026.8    0.05       0
Bank Sta=5022.8,5026.8
Exp/Cntr=0.3,0.1

Type RM Length L Ch R = 1,9667,152,152,152
BEGIN DESCRIPTION:
Elm 01 68 9667.29
END DESCRIPTION:
XS GIS Cut Line= 3
      1571536.79      6765791.22      1571759.21      6765793.39
      1572141.63      6765799.87
#Sta/Elev= 30
  4778.4 1976.91  4796.6 1975.50  4836.6 1973.60  4876.6 1972.47  4896.6 1972.27
  4906.6 1971.79  4916.6 1970.96  4926.6 1971.62  4936.6 1971.53  4946.6 1969.85
  4956.3 1968.97  5004.6 1968.04  5004.9 1967.54  5008.4 1967.54  5008.6 1968.04
  5026.6 1968.22  5056.6 1969.34  5066.6 1970.51  5076.6 1970.99  5086.6 1970.79
  5116.6 1971.28  5136.6 1972.29  5146.6 1973.03  5156.6 1973.34  5176.6 1972.89
  5216.6 1973.90  5236.7 1975.01  5256.7 1975.69  5356.7 1977.06  5383.3 1977.65
#Mann=3,-1,0
  4778.4    0.05       0  5004.6    0.05       0  5008.6    0.05       0
Bank Sta=5004.6,5008.6
Exp/Cntr=0.3,0.1

Type RM Length L Ch R = 1,9515,141,141,141
BEGIN DESCRIPTION:
Elm 01 68 9515.37
END DESCRIPTION:
XS GIS Cut Line= 3
      1571515.09      6765956.15      1571754.65      6765944.87
      1572116.62      6765946.60
#Sta/Elev= 30
  4759.4 1976.45  4769.3 1976.33  4799.4 1973.54  4809.4 1972.97  4825.4 1972.33
  4849.4 1972.31  4859.4 1970.88  4879.4 1972.01  4889.5 1970.30  4899.5 1969.46
  4969.5 1967.21  4987.6 1967.11  4987.8 1966.61  4991.3 1966.61  4991.6 1967.11
  5001.9 1967.24  5059.6 1969.13  5069.6 1969.81  5079.6 1971.01  5089.6 1970.57
  5119.6 1971.10  5149.6 1972.88  5159.6 1973.18  5189.6 1973.06  5219.6 1974.32
  5239.6 1975.51  5269.6 1975.93  5279.6 1975.85  5319.6 1977.01  5361.2 1977.81
#Mann=3,-1,0
  4759.4    0.05       0  4987.6    0.05       0  4991.6    0.05       0
Bank Sta=4987.6,4991.6
Exp/Cntr=0.3,0.1

Type RM Length L Ch R = 1,9374,219,219,219
BEGIN DESCRIPTION:
Elm 01 68 9373.68
END DESCRIPTION:
XS GIS Cut Line= 3
      1571519.97      6766078.46      1571706.56      6766070.86
      1572100.76      6766077.36
#Sta/Elev= 30
  4813.7 1974.98  4828.7 1974.73  4848.8 1972.21  4868.8 1971.39  4878.8 1970.57
  4888.8 1971.39  4898.8 1971.75  4908.8 1969.70  4945.9 1967.83  4950.9 1967.97
  4997.2 1966.63  5016.9 1966.55  5017.1 1966.05  5020.6 1966.05  5020.9 1966.55
  5078.9 1967.77  5098.9 1967.93  5132.0 1968.62  5148.9 1970.49  5158.9 1969.29
  5168.9 1970.55  5188.9 1971.37  5208.9 1972.76  5238.9 1972.99  5258.9 1973.67
  5288.9 1975.49  5308.9 1975.63  5338.9 1976.32  5388.9 1977.79  5394.7 1978.22
#Mann=3,-1,0
  4813.7    0.05       0  5016.9    0.05       0  5020.9    0.05       0
Bank Sta=5016.9,5020.9
Exp/Cntr=0.3,0.1

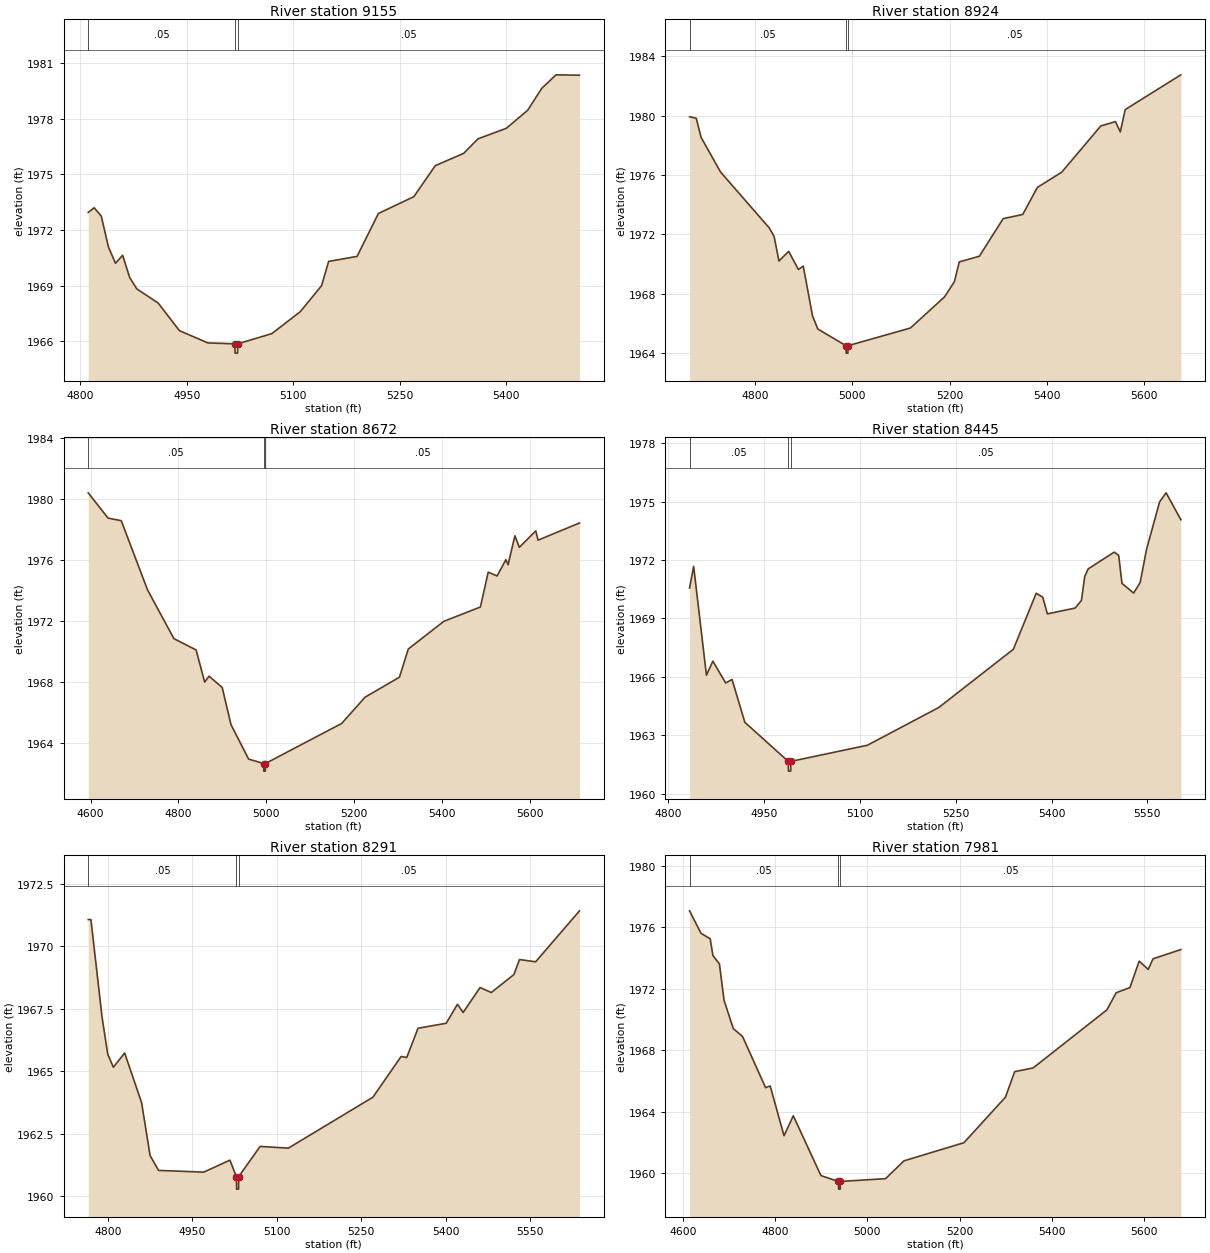
Type RM Length L Ch R = 1,9155,231,231,231
BEGIN DESCRIPTION:
Elm 01 68 9154.58
END DESCRIPTION:
XS GIS Cut Line= 3
      1571516.61      6766292.58      1571705.40      6766289.98
      1572208.01      6766280.86
#Sta/Elev= 30
  4811.5 1972.95  4819.9 1973.20  4829.9 1972.75  4839.9 1971.09  4849.9 1970.21
  4859.9 1970.64  4869.9 1969.44  4879.9 1968.83  4909.9 1968.07  4939.9 1966.58
  4979.9 1965.92  5017.9 1965.87  5018.2 1965.37  5021.7 1965.37  5021.9 1965.87
  5069.9 1966.42  5109.9 1967.60  5139.9 1969.00  5149.9 1970.31  5189.9 1970.58
  5219.9 1972.89  5269.9 1973.80  5300.0 1975.47  5340.0 1976.13  5360.0 1976.91
  5400.0 1977.48  5430.0 1978.45  5450.0 1979.64  5470.0 1980.36  5503.0 1980.34
#Mann=3,-1,0
  4811.5    0.05       0  5017.9    0.05       0  5021.9    0.05       0
Bank Sta=5017.9,5021.9
Exp/Cntr=0.3,0.1

Type RM Length L Ch R = 1,8924,252,252,252
BEGIN DESCRIPTION:
Elm 01 68 8924.32
END DESCRIPTION:
XS GIS Cut Line= 3
      1571321.28      6766497.01      1571655.92      6766504.82
      1572329.05      6766447.53
#Sta/Elev= 30
  4665.3 1979.92  4679.0 1979.82  4689.0 1978.53  4729.0 1976.20  4829.1 1972.44
  4839.1 1971.87  4849.1 1970.21  4869.1 1970.86  4889.1 1969.64  4899.1 1969.87
  4918.1 1966.52  4929.1 1965.63  4987.1 1964.51  4987.4 1964.01  4990.9 1964.01
  4991.1 1964.51  5119.5 1965.70  5189.8 1967.80  5209.9 1968.82  5219.9 1970.15
  5261.2 1970.53  5310.2 1973.06  5350.4 1973.34  5380.5 1975.16  5430.7 1976.19
  5511.0 1979.30  5541.1 1979.59  5551.1 1978.90  5561.1 1980.40  5675.6 1982.74
#Mann=3,-1,0
  4665.3    0.05       0  4987.1    0.05       0  4991.1    0.05       0
Bank Sta=4987.1,4991.1
Exp/Cntr=0.3,0.1

Type RM Length L Ch R = 1,8672,227,227,227
BEGIN DESCRIPTION:
Elm 01 68 8671.99
END DESCRIPTION:
XS GIS Cut Line= 3
      1571249.85      6766771.31      1571652.67      6766757.42
      1572360.52      6766648.12
#Sta/Elev= 30
  4594.5 1980.42  4639.7 1978.76  4669.7 1978.59  4729.7 1974.04  4789.8 1970.84
  4840.3 1970.10  4859.8 1967.99  4869.8 1968.38  4899.8 1967.63  4919.8 1965.19
  4959.9 1962.93  4994.2 1962.64  4994.5 1962.14  4998.0 1962.14  4998.2 1962.64
  5171.9 1965.27  5225.4 1967.00  5303.5 1968.31  5323.7 1970.16  5404.7 1971.98
  5488.0 1972.92  5505.8 1975.21  5526.1 1974.96  5546.0 1976.03  5551.1 1975.70
  5566.6 1977.60  5576.7 1976.84  5614.2 1977.92  5619.3 1977.31  5713.8 1978.44
#Mann=3,-1,0
  4594.5    0.05       0  4994.2    0.05       0  4998.2    0.05       0
Bank Sta=4994.2,4998.2
Exp/Cntr=0.3,0.1

Type RM Length L Ch R = 1,8445,154,154,154
BEGIN DESCRIPTION:
Elm 01 68 8445.05
END DESCRIPTION:
XS GIS Cut Line= 3
      1571488.57      6766989.20      1571655.27      6766983.99
      1572247.71      6766875.91
#Sta/Elev= 30
  4833.4 1970.56  4839.8 1971.67  4859.8 1966.08  4869.9 1966.80  4889.9 1965.68
  4899.9 1965.86  4919.9 1963.66  4987.9 1961.65  4988.2 1961.15  4991.7 1961.15
  4991.9 1961.65  5111.7 1962.48  5223.5 1964.42  5340.2 1967.41  5376.0 1970.29
  5386.2 1970.09  5393.5 1969.23  5437.0 1969.53  5446.8 1969.92  5451.9 1971.15
  5457.3 1971.54  5498.0 1972.40  5505.1 1972.24  5510.2 1970.80  5528.5 1970.30
  5538.7 1970.84  5548.8 1972.56  5569.2 1974.99  5579.3 1975.45  5602.4 1974.07
#Mann=3,-1,0
  4833.4    0.05       0  4987.9    0.05       0  4991.9    0.05       0
Bank Sta=4987.9,4991.9
Exp/Cntr=0.3,0.1

Type RM Length L Ch R = 1,8291,310,310,310
BEGIN DESCRIPTION:
Elm 01 68 8291.06
END DESCRIPTION:
XS GIS Cut Line= 3
      1571470.42      6767105.08      1571704.75      6767122.01
      1572341.35      6767157.08
#Sta/Elev= 30
  4765.1 1971.07  4769.9 1971.07  4789.7 1967.16  4799.8 1965.68  4809.8 1965.16
  4829.8 1965.73  4859.9 1963.74  4875.0 1961.62  4890.0 1961.03  4970.2 1960.96
  5016.7 1961.44  5028.3 1960.78  5028.6 1960.28  5032.1 1960.28  5032.3 1960.78
  5070.4 1961.99  5120.5 1961.92  5270.7 1963.96  5320.8 1965.59  5330.8 1965.55
  5350.8 1966.72  5400.9 1966.92  5420.9 1967.68  5430.9 1967.35  5461.0 1968.35
  5481.0 1968.15  5521.1 1968.87  5531.1 1969.47  5559.7 1969.38  5637.6 1971.42
#Mann=3,-1,0
  4765.1    0.05       0  5028.3    0.05       0  5032.3    0.05       0
Bank Sta=5028.3,5032.3
Exp/Cntr=0.3,0.1

Type RM Length L Ch R = 1,7981,358,358,358
BEGIN DESCRIPTION:
Elm 01 68 7981.43
END DESCRIPTION:
XS GIS Cut Line= 3
      1571310.22      6767355.08      1571695.64      6767339.45
      1572375.36      6767321.22
#Sta/Elev= 30
  4614.4 1977.07  4639.2 1975.61  4659.2 1975.25  4665.0 1974.17  4679.2 1973.61
  4689.2 1971.25  4709.3 1969.41  4729.3 1968.90  4779.3 1965.57  4789.3 1965.68
  4819.3 1962.44  4839.4 1963.74  4899.4 1959.85  4937.4 1959.47  4937.7 1958.97
  4941.2 1958.97  4941.4 1959.47  5039.5 1959.65  5079.5 1960.81  5209.6 1961.99
  5299.6 1964.95  5319.6 1966.61  5359.6 1966.85  5519.7 1970.63  5539.7 1971.74
  5569.7 1972.08  5589.7 1973.80  5609.3 1973.26  5619.7 1973.95  5680.1 1974.55
#Mann=3,-1,0
  4614.4    0.05       0  4937.4    0.05       0  4941.4    0.05       0
Bank Sta=4937.4,4941.4
Exp/Cntr=0.3,0.1

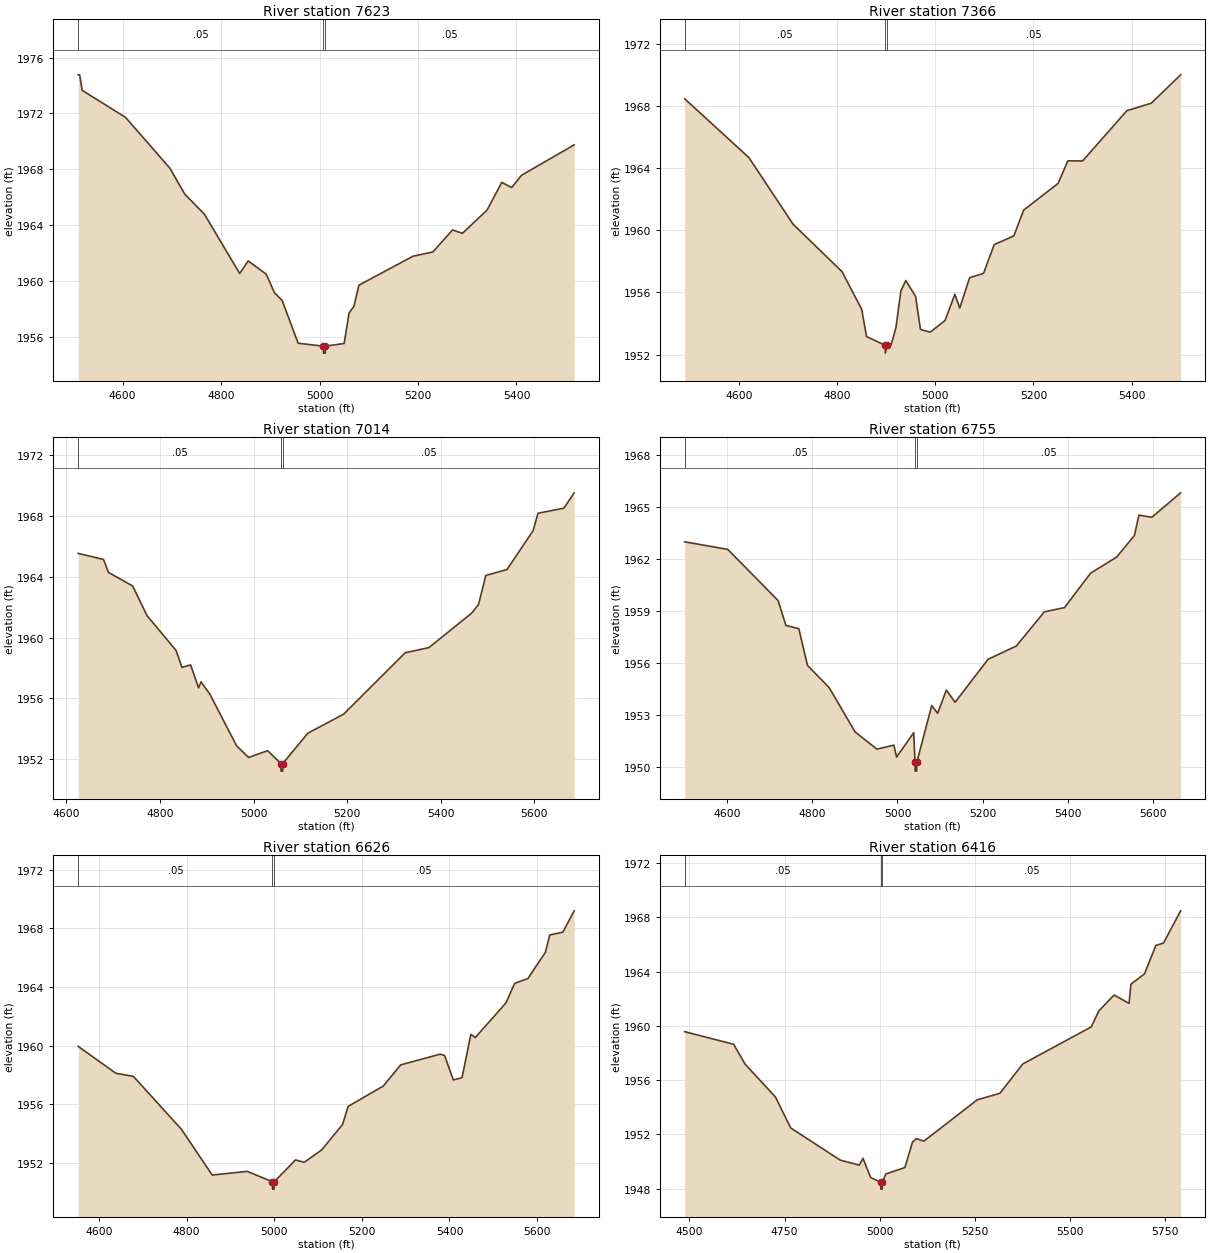
Type RM Length L Ch R = 1,7623,257,257,257
BEGIN DESCRIPTION:
Elm 01 68 7623.05
END DESCRIPTION:
XS GIS Cut Line= 4
      1571188.89      6767542.75      1571496.16      6767558.38
      1571666.30      6767627.82      1572181.80      6767603.60
#Sta/Elev= 30
  4509.7 1974.77  4512.7 1974.77  4517.7 1973.66  4605.9 1971.72  4696.1 1968.07
  4726.1 1966.22  4766.1 1964.78  4837.7 1960.53  4855.0 1961.43  4891.7 1960.48
  4908.5 1959.14  4924.1 1958.59  4956.5 1955.53  5007.8 1955.32  5008.1 1954.82
  5011.6 1954.82  5011.8 1955.32  5049.9 1955.51  5059.9 1957.69  5069.9 1958.18
  5079.9 1959.69  5190.0 1961.77  5230.1 1962.07  5270.1 1963.65  5290.2 1963.41
  5340.2 1965.07  5370.2 1967.06  5390.3 1966.69  5410.3 1967.57  5517.2 1969.75
#Mann=3,-1,0
  4509.7    0.05       0  5007.8    0.05       0  5011.8    0.05       0
Bank Sta=5007.8,5011.8
Exp/Cntr=0.3,0.1

Type RM Length L Ch R = 1,7366,352,352,352
BEGIN DESCRIPTION:
Elm 01 68 7365.61
END DESCRIPTION:
XS GIS Cut Line= 3
      1571194.06      6767827.47      1571707.96      6767829.21
      1572204.47      6767797.96
#Sta/Elev= 30
  4488.7 1968.45  4619.6 1964.67  4709.6 1960.39  4809.6 1957.33  4849.6 1954.92
  4859.6 1953.16  4897.6 1952.59  4897.9 1952.09  4901.6 1952.59  4909.6 1952.61
  4919.6 1953.74  4929.6 1956.09  4939.6 1956.76  4959.6 1955.74  4969.6 1953.61
  4989.6 1953.44  5019.7 1954.19  5039.7 1955.87  5049.7 1954.99  5069.8 1956.94
  5098.2 1957.22  5119.9 1959.07  5160.0 1959.63  5180.0 1961.29  5250.1 1963.00
  5270.2 1964.46  5300.2 1964.45  5390.4 1967.68  5440.5 1968.17  5500.1 1969.99
#Mann=3,-1,0
  4488.7    0.05       0  4897.6    0.03       0  4901.6    0.05       0
Bank Sta=4897.6,4901.6
Exp/Cntr=0.3,0.1

Type RM Length L Ch R = 1,7014,259,259,259
BEGIN DESCRIPTION:
Elm 01 68 7013.88
END DESCRIPTION:
XS GIS Cut Line= 3
      1571202.42      6768038.24      1571565.26      6768131.99
      1572241.18      6768019.33
#Sta/Elev= 30
  4625.1 1965.53  4679.2 1965.13  4689.7 1964.28  4741.4 1963.39  4772.4 1961.43
  4834.3 1959.15  4846.9 1958.04  4865.3 1958.20  4882.4 1956.69  4887.6 1957.09
  4906.6 1956.27  4963.7 1952.88  4989.3 1952.12  5030.0 1952.56  5058.4 1951.72
  5058.7 1951.22  5062.2 1951.22  5062.4 1951.72  5115.8 1953.71  5192.2 1954.96
  5324.0 1959.00  5374.7 1959.34  5465.9 1961.60  5480.7 1962.17  5496.3 1964.08
  5541.6 1964.47  5597.3 1967.02  5607.9 1968.17  5663.2 1968.50  5685.1 1969.51
#Mann=3,-1,0
  4625.1    0.05       0  5058.4    0.05       0  5062.4    0.05       0
Bank Sta=5058.4,5062.4
Exp/Cntr=0.3,0.1

Type RM Length L Ch R = 1,6755,129,129,129
BEGIN DESCRIPTION:
Elm 01 68 6754.58
END DESCRIPTION:
XS GIS Cut Line= 3
      1571120.85      6768255.26      1571612.13      6768342.06
      1572260.73      6768189.45
#Sta/Elev= 30
  4500.1 1963.00  4601.4 1962.56  4719.8 1959.60  4737.9 1958.17  4768.3 1957.98
  4788.6 1955.86  4839.4 1954.58  4900.4 1952.02  4951.6 1951.02  4991.7 1951.25
  4997.9 1950.56  5038.2 1951.97  5041.3 1950.25  5041.6 1949.75  5045.1 1949.75
  5045.3 1950.25  5080.6 1953.54  5094.4 1953.09  5114.9 1954.43  5135.5 1953.73
  5212.9 1956.21  5279.3 1956.98  5345.1 1958.95  5392.6 1959.20  5453.9 1961.19
  5514.6 1962.11  5556.7 1963.36  5567.3 1964.54  5597.8 1964.42  5665.3 1965.83
#Mann=3,-1,0
  4500.1    0.05       0  5041.3    0.05       0  5045.3    0.05       0
Bank Sta=5041.3,5045.3
Exp/Cntr=0.3,0.1

Type RM Length L Ch R = 1,6626,210,210,210
BEGIN DESCRIPTION:
Elm 01 68 6625.94
END DESCRIPTION:
XS GIS Cut Line= 3
      1571249.24      6768447.79      1571698.94      6768437.37
      1572380.65      6768418.29
#Sta/Elev= 30
  4552.7 1959.96  4638.5 1958.13  4678.5 1957.92  4788.5 1954.30  4858.5 1951.19
  4938.6 1951.44  4996.0 1950.73  4996.3 1950.23  4999.8 1950.23  5000.0 1950.73
  5048.6 1952.22  5068.6 1952.06  5108.6 1952.91  5156.2 1954.65  5168.6 1955.87
  5248.7 1957.25  5288.7 1958.70  5378.7 1959.43  5388.7 1959.35  5408.7 1957.67
  5428.7 1957.83  5448.8 1960.78  5458.8 1960.56  5528.8 1962.92  5548.8 1964.26
  5578.8 1964.58  5618.8 1966.37  5628.8 1967.55  5658.8 1967.75  5684.5 1969.20
#Mann=3,-1,0
  4552.7    0.05       0  4996.0    0.05       0  5000.0    0.05       0
Bank Sta=4996,5000
Exp/Cntr=0.3,0.1

Type RM Length L Ch R = 1,6416,199,199,199
BEGIN DESCRIPTION:
Elm 01 68 6416
END DESCRIPTION:
XS GIS Cut Line= 3
      1571176.38      6768602.30      1571688.52      6768623.13
      1572479.96      6768610.99
#Sta/Elev= 30
  4487.4 1959.58  4616.1 1958.65  4646.2 1957.19  4726.2 1954.76  4766.2 1952.48
  4896.4 1950.11  4946.4 1949.74  4956.4 1950.24  4976.4 1948.83  5003.1 1948.47
  5003.3 1947.97  5006.8 1947.97  5007.1 1948.47  5016.4 1949.09  5066.5 1949.56
  5086.5 1951.44  5096.5 1951.69  5116.5 1951.51  5256.5 1954.55  5316.5 1955.04
  5376.5 1957.20  5556.5 1959.93  5576.5 1961.11  5616.5 1962.28  5655.9 1961.67
  5660.9 1963.08  5696.5 1963.84  5726.5 1965.94  5746.5 1966.11  5791.5 1968.49
#Mann=3,-1,0
  4487.4    0.05       0  5003.1    0.03       0  5007.1    0.05       0
Bank Sta=5003.1,5007.1
Exp/Cntr=0.3,0.1

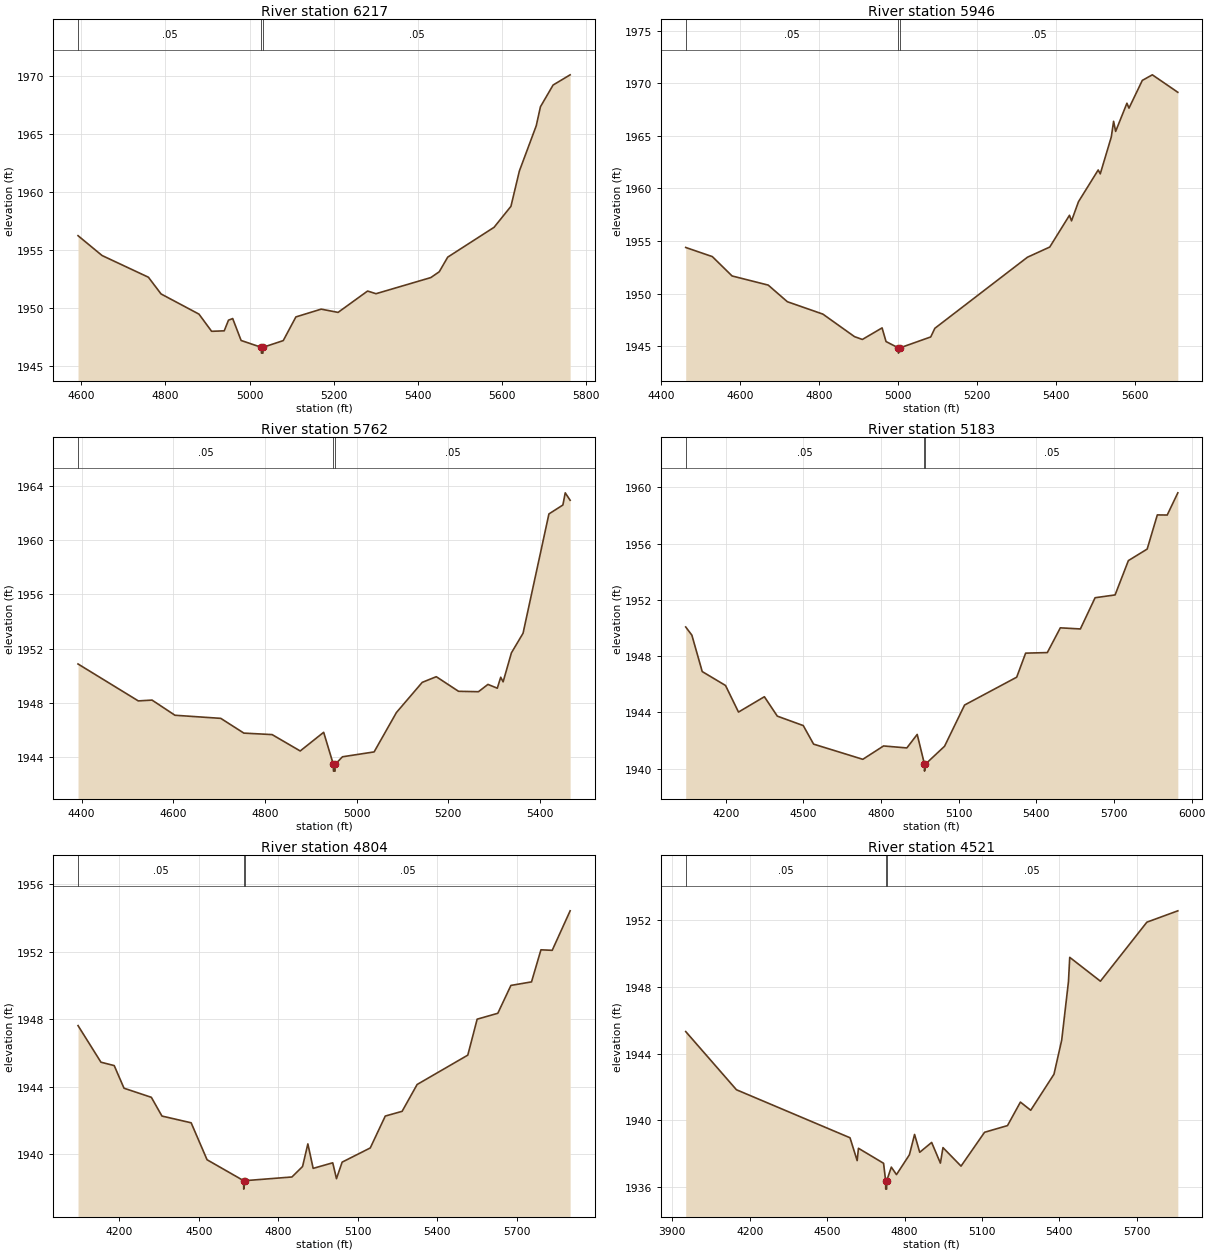
Type RM Length L Ch R = 1,6217,271,271,271
BEGIN DESCRIPTION:
Elm 01 68 6216.7
END DESCRIPTION:
XS GIS Cut Line= 3
      1571347.90      6768818.01      1571755.88      6768802.82
      1572515.40      6768761.59
#Sta/Elev= 30
  4592.5 1956.26  4649.6 1954.55  4759.7 1952.68  4789.7 1951.24  4879.8 1949.50
  4909.8 1948.02  4939.8 1948.06  4949.9 1948.98  4959.9 1949.12  4979.9 1947.23
  5027.9 1946.64  5028.2 1946.14  5031.7 1946.14  5031.9 1946.64  5080.0 1947.22
  5110.0 1949.26  5170.1 1949.93  5210.2 1949.65  5280.3 1951.49  5300.3 1951.26
  5430.5 1952.65  5450.5 1953.15  5470.6 1954.41  5580.7 1956.98  5620.8 1958.79
  5640.8 1961.83  5680.9 1965.73  5690.9 1967.37  5720.9 1969.24  5761.4 1970.12
#Mann=3,-1,0
  4592.5    0.05       0  5027.9    0.05       0  5031.9    0.05       0
Bank Sta=5027.9,5031.9
Exp/Cntr=0.3,0.1

Type RM Length L Ch R = 1,5946,184,184,184
BEGIN DESCRIPTION:
Elm 01 68 5945.81
END DESCRIPTION:
XS GIS Cut Line= 3
      1571317.52      6769026.35      1571853.54      6769043.71
      1572537.09      6768848.41
#Sta/Elev= 30
  4462.2 1954.39  4529.7 1953.52  4579.7 1951.68  4671.3 1950.81  4719.8 1949.23
  4809.9 1948.05  4889.9 1945.91  4909.9 1945.64  4959.9 1946.74  4969.9 1945.44
  5001.1 1944.84  5001.4 1944.34  5005.1 1944.84  5083.2 1945.88  5093.6 1946.70
  5328.2 1953.46  5384.8 1954.43  5434.8 1957.45  5440.0 1956.92  5457.6 1958.74
  5507.6 1961.76  5512.8 1961.39  5540.8 1964.90  5546.6 1966.39  5551.8 1965.43
  5580.4 1968.11  5585.6 1967.64  5619.4 1970.28  5644.8 1970.81  5709.4 1969.15
#Mann=3,-1,0
  4462.2    0.05       0  5001.1    0.05       0  5005.1    0.05       0
Bank Sta=5001.1,5005.1
Exp/Cntr=0.3,0.1

Type RM Length L Ch R = 1,5762,579,579,579
BEGIN DESCRIPTION:
Mapping XS 5ad1e1b1
END DESCRIPTION:
XS GIS Cut Line= 3
      1571343.37      6769249.02      1571688.41      6769249.02
      1572400.15      6769090.61
#Sta/Elev= 30
  4392.1 1950.86  4523.7 1948.13  4553.7 1948.19  4603.7 1947.07  4703.7 1946.84
  4754.1 1945.75  4815.8 1945.64  4877.1 1944.43  4928.3 1945.81  4949.4 1943.44
  4949.7 1942.94  4953.2 1942.94  4953.4 1943.44  4969.3 1944.00  5038.4 1944.36
  5087.1 1947.27  5143.4 1949.50  5174.1 1949.92  5222.7 1948.84  5266.2 1948.81
  5286.9 1949.35  5307.3 1949.07  5314.8 1949.88  5320.0 1949.54  5338.1 1951.68
  5363.5 1953.13  5420.0 1961.95  5450.5 1962.61  5455.6 1963.51  5466.3 1962.96
#Mann=3,-1,0
  4392.1    0.05       0  4949.4    0.05       0  4953.4    0.05       0
Bank Sta=4949.4,4953.4
Exp/Cntr=0.3,0.1

Type RM Length L Ch R = 1,5183,379,379,379
BEGIN DESCRIPTION:
Elm 01 68 5182.79
END DESCRIPTION:
XS GIS Cut Line= 3
      1571051.24      6769700.41      1572004.94      6769731.36
      1572851.70      6769307.99
#Sta/Elev= 30
  4045.8 1950.08  4069.6 1949.50  4109.6 1946.91  4199.6 1945.92  4249.7 1944.03
  4349.7 1945.12  4399.7 1943.74  4499.8 1943.07  4539.8 1941.75  4729.9 1940.67
  4810.0 1941.62  4900.0 1941.48  4940.0 1942.44  4968.0 1940.33  4968.3 1939.83
  4972.0 1940.33  5045.7 1941.60  5123.0 1944.53  5324.3 1946.51  5358.8 1948.22
  5442.6 1948.26  5492.9 1950.02  5570.3 1949.94  5627.1 1952.16  5704.4 1952.36
  5755.7 1954.80  5828.3 1955.62  5867.5 1958.05  5905.7 1958.04  5946.7 1959.62
#Mann=3,-1,0
  4045.8    0.05       0  4968.0    0.05       0  4972.0    0.05       0
Bank Sta=4968,4972
Exp/Cntr=0.3,0.1

Type RM Length L Ch R = 1,4804,283,283,283
BEGIN DESCRIPTION:
Elm 01 68 4803.71
END DESCRIPTION:
XS GIS Cut Line= 3
      1571108.54      6770117.07      1572061.35      6770094.92
      1572711.19      6769468.47
#Sta/Elev= 30
  4044.8 1947.63  4131.3 1945.46  4181.3 1945.26  4218.2 1943.92  4321.3 1943.38
  4361.3 1942.27  4471.4 1941.87  4531.4 1939.68  4669.4 1938.44  4669.7 1937.94
  4673.4 1938.44  4851.5 1938.66  4891.5 1939.28  4911.5 1940.62  4931.5 1939.17
  5005.3 1939.50  5019.4 1938.56  5040.8 1939.54  5146.8 1940.38  5203.4 1942.27
  5266.9 1942.55  5323.5 1944.14  5514.6 1945.88  5549.9 1948.01  5627.8 1948.36
  5677.2 1950.01  5754.9 1950.22  5790.4 1952.12  5832.9 1952.09  5900.5 1954.43
#Mann=3,-1,0
  4044.8    0.05       0  4669.4    0.03       0  4673.4    0.05       0
Bank Sta=4669.4,4673.4
Exp/Cntr=0.3,0.1

Type RM Length L Ch R = 1,4521,448,448,448
BEGIN DESCRIPTION:
Elm 01 68 4743.735
END DESCRIPTION:
XS GIS Cut Line= 3
      1571108.55      6770309.78      1572155.42      6770346.24
      1573014.82      6770320.20
#Sta/Elev= 30
  3951.8 1945.32  4148.4 1941.83  4588.6 1938.95  4616.3 1937.58  4621.3 1938.32
  4718.7 1937.42  4726.7 1936.37  4727.0 1935.87  4730.5 1935.87  4730.7 1936.37
  4748.7 1937.19  4768.7 1936.74  4818.8 1937.93  4838.8 1939.15  4858.8 1938.08
  4905.0 1938.67  4938.9 1937.43  4948.9 1938.36  5018.9 1937.25  5110.1 1939.28
  5199.0 1939.68  5249.0 1941.09  5289.0 1940.60  5379.1 1942.76  5409.1 1944.81
  5435.2 1948.31  5440.2 1949.77  5559.1 1948.34  5739.2 1951.88  5859.1 1952.56
#Mann=3,-1,0
  3951.8    0.05       0  4726.7    0.03       0  4730.7    0.05       0
Bank Sta=4726.7,4730.7
Exp/Cntr=0.3,0.1

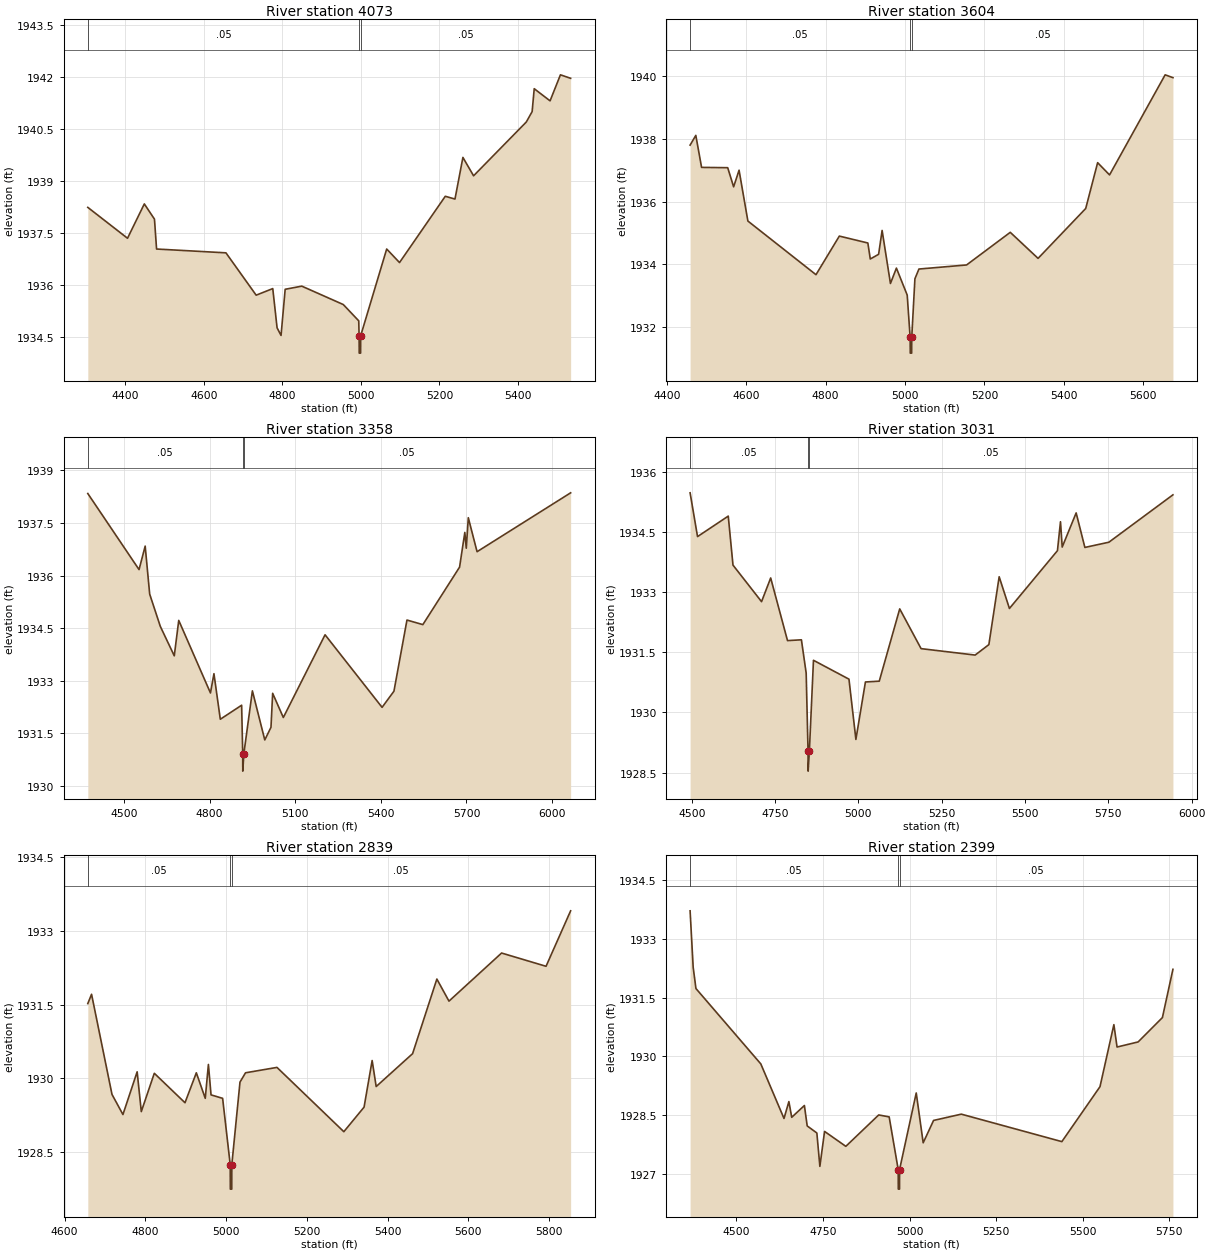
Type RM Length L Ch R = 1,4073,469,469,469
BEGIN DESCRIPTION:
Elm 01 68 4073.04
END DESCRIPTION:
XS GIS Cut Line= 3
      1571439.34      6770517.74      1572095.64      6770743.45
      1572626.93      6770816.37
#Sta/Elev= 30
  4304.1 1938.24  4405.3 1937.35  4448.1 1938.34  4474.0 1937.90  4479.3 1937.04
  4656.1 1936.93  4733.1 1935.71  4775.4 1935.90  4786.4 1934.77  4796.5 1934.55
  4807.0 1935.88  4849.4 1935.97  4955.1 1935.44  4994.5 1934.97  4995.4 1934.54
  4995.7 1934.04  4999.2 1934.04  4999.4 1934.54  5065.7 1937.04  5098.4 1936.65
  5215.0 1938.56  5239.7 1938.48  5259.9 1939.68  5287.1 1939.15  5421.4 1940.70
  5436.3 1941.00  5441.6 1941.66  5482.0 1941.31  5508.4 1942.06  5534.4 1941.96
#Mann=3,-1,0
  4304.1    0.05       0  4995.4    0.05       0  4999.4    0.05       0
Bank Sta=4995.4,4999.4
Exp/Cntr=0.3,0.1

Type RM Length L Ch R = 1,3604,246,246,246
BEGIN DESCRIPTION:
Elm 01 68 3604.05
END DESCRIPTION:
XS GIS Cut Line= 3
      1571283.14      6770708.73      1571731.05      6771014.28
      1572404.62      6771021.22
#Sta/Elev= 30
  4458.7 1937.80  4473.1 1938.11  4487.6 1937.09  4553.4 1937.08  4568.3 1936.47
  4582.0 1937.00  4604.2 1935.38  4775.7 1933.67  4834.5 1934.90  4906.3 1934.68
  4912.4 1934.17  4933.4 1934.32  4942.2 1935.08  4963.2 1933.39  4978.2 1933.88
  5005.4 1933.02  5012.8 1931.67  5013.1 1931.17  5016.6 1931.17  5016.8 1931.67
  5024.8 1933.54  5034.9 1933.85  5154.9 1933.98  5264.9 1935.02  5334.9 1934.19
  5454.9 1935.78  5484.9 1937.24  5514.9 1936.85  5654.9 1940.04  5674.5 1939.95
#Mann=3,-1,0
  4458.7    0.05       0  5012.8    0.05       0  5016.8    0.05       0
Bank Sta=5012.8,5016.8
Exp/Cntr=0.3,0.1

Type RM Length L Ch R = 1,3358,327,327,327
BEGIN DESCRIPTION:
Mapping XS cb444b95
END DESCRIPTION:
XS GIS Cut Line= 4
      1571063.34      6770903.70      1571440.90      6771122.86
      1571963.90      6771415.83      1572606.31      6771546.05
#Sta/Elev= 30
  4373.5 1938.34  4553.0 1936.17  4574.5 1936.84  4590.3 1935.47  4627.5 1934.55
  4676.4 1933.71  4692.1 1934.72  4803.2 1932.65  4815.4 1933.20  4837.7 1931.90
  4912.4 1932.30  4916.2 1930.92  4916.4 1930.42  4920.2 1930.92  4950.1 1932.71
  4993.5 1931.31  5015.2 1931.67  5021.1 1932.64  5058.5 1931.95  5204.7 1934.31
  5404.4 1932.24  5446.0 1932.70  5491.6 1934.73  5547.3 1934.60  5675.9 1936.24
  5694.3 1937.23  5699.4 1936.78  5706.5 1937.65  5737.2 1936.68  6065.0 1938.36
#Mann=3,-1,0
  4373.5    0.05       0  4916.2    0.05       0  4920.2    0.05       0
Bank Sta=4916.2,4920.2
Exp/Cntr=0.3,0.1

Type RM Length L Ch R = 1,3031,192,192,192
BEGIN DESCRIPTION:
Elm 01 68 3031.99
END DESCRIPTION:
XS GIS Cut Line= 3
      1571071.58      6771159.78      1571456.75      6771489.98
      1572371.81      6771711.40
#Sta/Elev= 30
  4495.0 1935.47  4517.3 1934.38  4609.5 1934.89  4623.7 1933.67  4709.4 1932.76
  4736.8 1933.35  4787.3 1931.79  4829.0 1931.81  4843.3 1930.98  4848.9 1929.04
  4849.2 1928.54  4852.9 1929.04  4865.2 1931.30  4971.7 1930.83  4992.5 1929.33
  5021.1 1930.76  5062.6 1930.78  5124.0 1932.58  5188.1 1931.59  5350.3 1931.43
  5391.5 1931.69  5422.4 1933.38  5453.2 1932.59  5597.3 1934.03  5606.4 1934.75
  5611.6 1934.12  5653.4 1934.97  5679.6 1934.11  5751.6 1934.24  5943.8 1935.42
#Mann=3,-1,0
  4495.0    0.05       0  4848.9    0.05       0  4852.9    0.05       0
Bank Sta=4848.9,4852.9
Exp/Cntr=0.3,0.1

Type RM Length L Ch R = 1,2839,440,440,440
BEGIN DESCRIPTION:
Mapping XS e8f9a0c3
END DESCRIPTION:
XS GIS Cut Line= 5
      1571067.66      6771472.28      1571153.57      6771539.96
      1571302.01      6771601.16      1571574.14      6771826.42
      1572145.75      6771860.27
#Sta/Elev= 30
  4657.4 1931.52  4666.7 1931.71  4717.3 1929.67  4744.4 1929.26  4779.6 1930.13
  4789.9 1929.32  4822.1 1930.10  4898.1 1929.50  4926.2 1930.11  4948.3 1929.59
  4956.1 1930.28  4962.6 1929.66  4991.3 1929.59  5010.1 1928.24  5010.4 1927.74
  5013.9 1927.74  5014.1 1928.24  5034.3 1929.92  5048.0 1930.11  5125.9 1930.22
  5291.5 1928.91  5341.6 1929.41  5361.6 1930.36  5371.6 1929.83  5461.8 1930.50
  5521.9 1932.02  5551.9 1931.57  5682.2 1932.55  5792.3 1932.28  5853.2 1933.41
#Mann=3,-1,0
  4657.4    0.05       0  5010.1    0.05       0  5014.1    0.05       0
Bank Sta=5010.1,5014.1
Exp/Cntr=0.3,0.1

Type RM Length L Ch R = 1,2399,0,0,0
BEGIN DESCRIPTION:
Elm 01 68 4245.326
END DESCRIPTION:
XS GIS Cut Line= 3
      1570807.08      6771442.93      1571063.73      6771954.02
      1571885.30      6772002.20
#Sta/Elev= 30
  4366.0 1933.71  4374.9 1932.27  4382.9 1931.73  4570.3 1929.81  4637.3 1928.42
  4651.4 1928.85  4659.6 1928.45  4696.2 1928.75  4704.3 1928.23  4732.2 1928.05
  4740.9 1927.20  4754.5 1928.09  4815.9 1927.71  4910.9 1928.51  4941.1 1928.46
  4967.2 1927.12  4967.5 1926.62  4971.0 1926.62  4971.2 1927.12  5019.3 1929.07
  5039.4 1927.80  5069.4 1928.37  5149.5 1928.53  5440.0 1927.83  5550.2 1929.23
  5590.3 1930.81  5599.5 1930.24  5660.4 1930.37  5730.5 1930.99  5760.9 1932.22
#Mann=3,-1,0
  4366.0    0.05       0  4967.2    0.05       0  4971.2    0.05       0
Bank Sta=4967.2,4971.2
Exp/Cntr=0.3,0.1

Chan Stop Cuts=-1