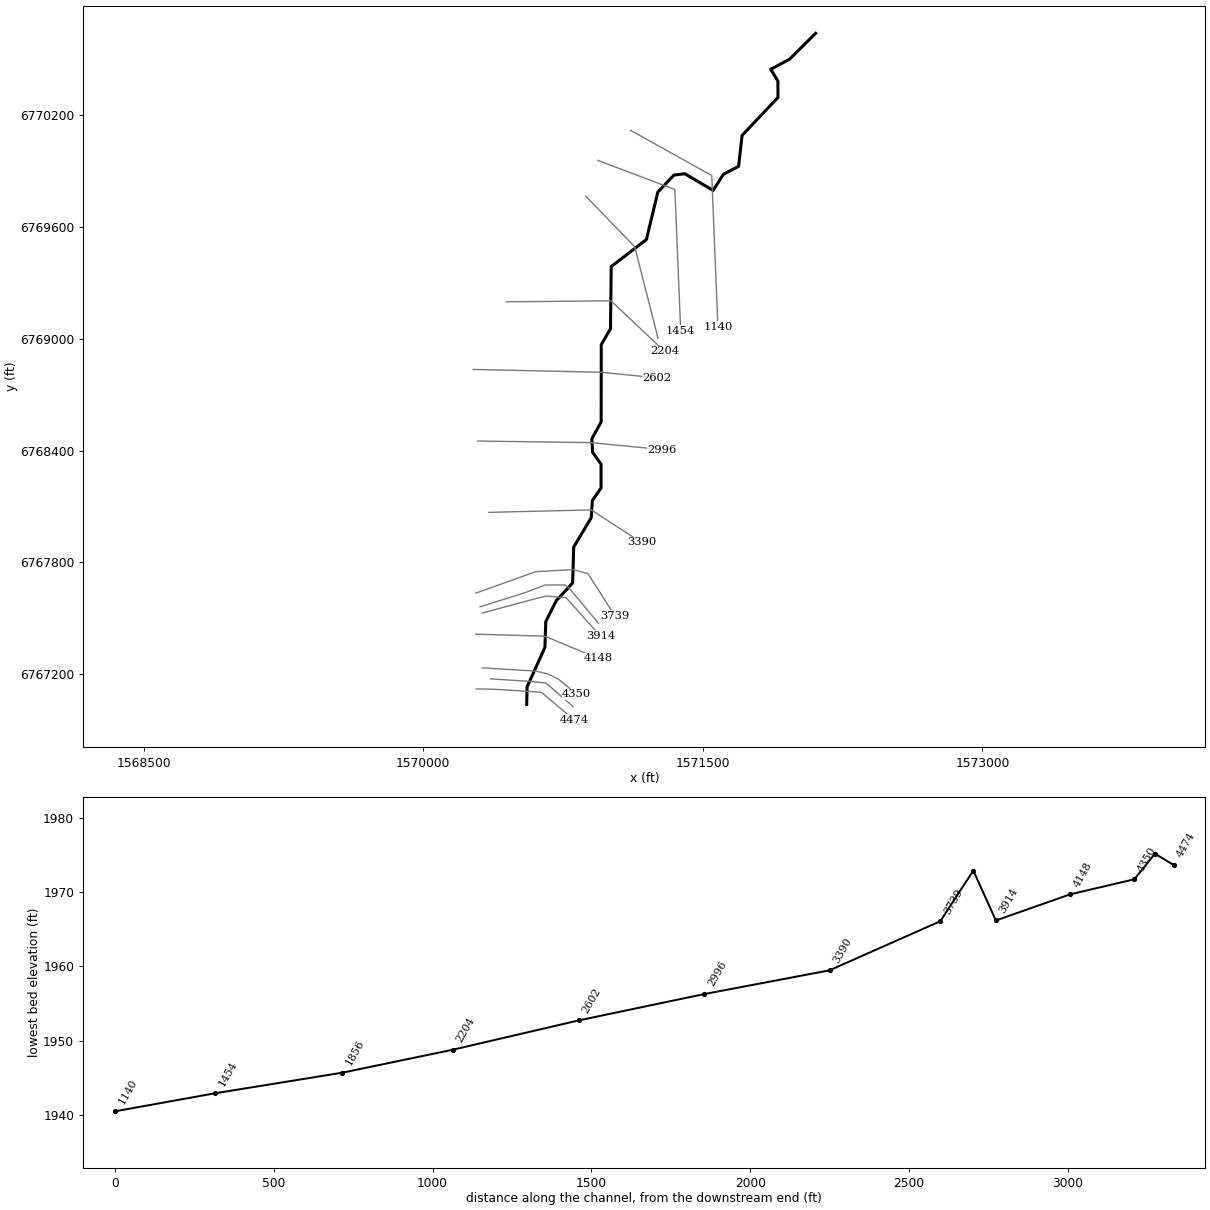
--- Elm 01 69.prj (project) ---

Proj Title=Elm 01 69 Base Level Engineering
Current Plan=p01
Default Exp/Contr=0.3,0.1
English Units
Geom File=g01
Flow File=f01
Plan File=p01
BEGIN DESCRIPTION:
Elm 01 69
END DESCRIPTION:

--- Elm 01 69.p01 (plan) ---

Plan Title=Multiple Run
Short Identifier=Multiple
Geom File=g01
Flow File=f01
Subcritical Flow
K Sum by GR= 0
Std Step Tol= 0.01
Critical Tol= 0.01
Num of Std Step Trials= 20
Max Error Tol= 0.3
Flow Tol Ratio= 0.001
Split Flow NTrial= 30
Split Flow Tol= 0.02
Split Flow Ratio= 0.02
Log Output Level= 0
Friction Slope Method= 1
Unsteady Friction Slope Method= 2
Unsteady Bridges Friction Slope Method= 1
Parabolic Critical Depth
Global Vel Dist=  1 , 1 , 1
Global Log Level= 0
CheckData=True
Encroach Param= -1, 0, 0, 0
BEGIN DESCRIPTION:
Multiple Run
END DESCRIPTION:

--- Elm 01 69.f01 (steady flow) ---

Flow Title=Multiple
Number of Profiles=7
Profile Names=10-year,25-year,50-year,1pct_min,100-year,1pct_plu,500-year
River Rch & RM= Elm 01 69,Reach-1,4474
      57      71      82      59      95     130     127
Boundary for River Rch & Prof#=Elm 01 69,Reach-1,1
Up Type=0
Dn Type=3
Dn Slope=0.001
Boundary for River Rch & Prof#=Elm 01 69,Reach-1,2
Up Type=0
Dn Type=3
Dn Slope=0.001
Boundary for River Rch & Prof#=Elm 01 69,Reach-1,3
Up Type=0
Dn Type=3
Dn Slope=0.001
Boundary for River Rch & Prof#=Elm 01 69,Reach-1,4
Up Type=0
Dn Type=3
Dn Slope=0.001
Boundary for River Rch & Prof#=Elm 01 69,Reach-1,5
Up Type=0
Dn Type=3
Dn Slope=0.001
Boundary for River Rch & Prof#=Elm 01 69,Reach-1,6
Up Type=0
Dn Type=3
Dn Slope=0.001
Boundary for River Rch & Prof#=Elm 01 69,Reach-1,7
Up Type=0
Dn Type=3
Dn Slope=0.001

--- Elm 01 69.g01 (geometry) ---

Geom Title=Existing Conditions

River Reach=Elm 01 69,Reach-1
Reach XY= 30
      1570555.00      6767038.00      1570557.10      6767132.13
      1570652.73      6767343.94      1570657.25      6767482.07
      1570713.16      6767594.05      1570801.45      6767689.47
      1570807.24      6767882.07      1570901.17      6768039.58
      1570907.36      6768132.02      1570953.80      6768198.51
      1570953.79      6768327.49      1570908.71      6768389.60
      1570904.60      6768463.00      1570954.48      6768553.22
      1570955.07      6768967.97      1571004.48      6769053.22
      1571008.45      6769386.75      1571197.15      6769531.81
      1571258.61      6769786.52      1571345.29      6769877.82
      1571403.26      6769884.69      1571555.29      6769795.23
      1571610.65      6769882.30      1571691.71      6769924.36
      1571710.47      6770090.45      1571903.03      6770293.89
      1571902.63      6770382.12      1571864.01      6770445.02
      1571964.65      6770498.77      1572105.00      6770638.00

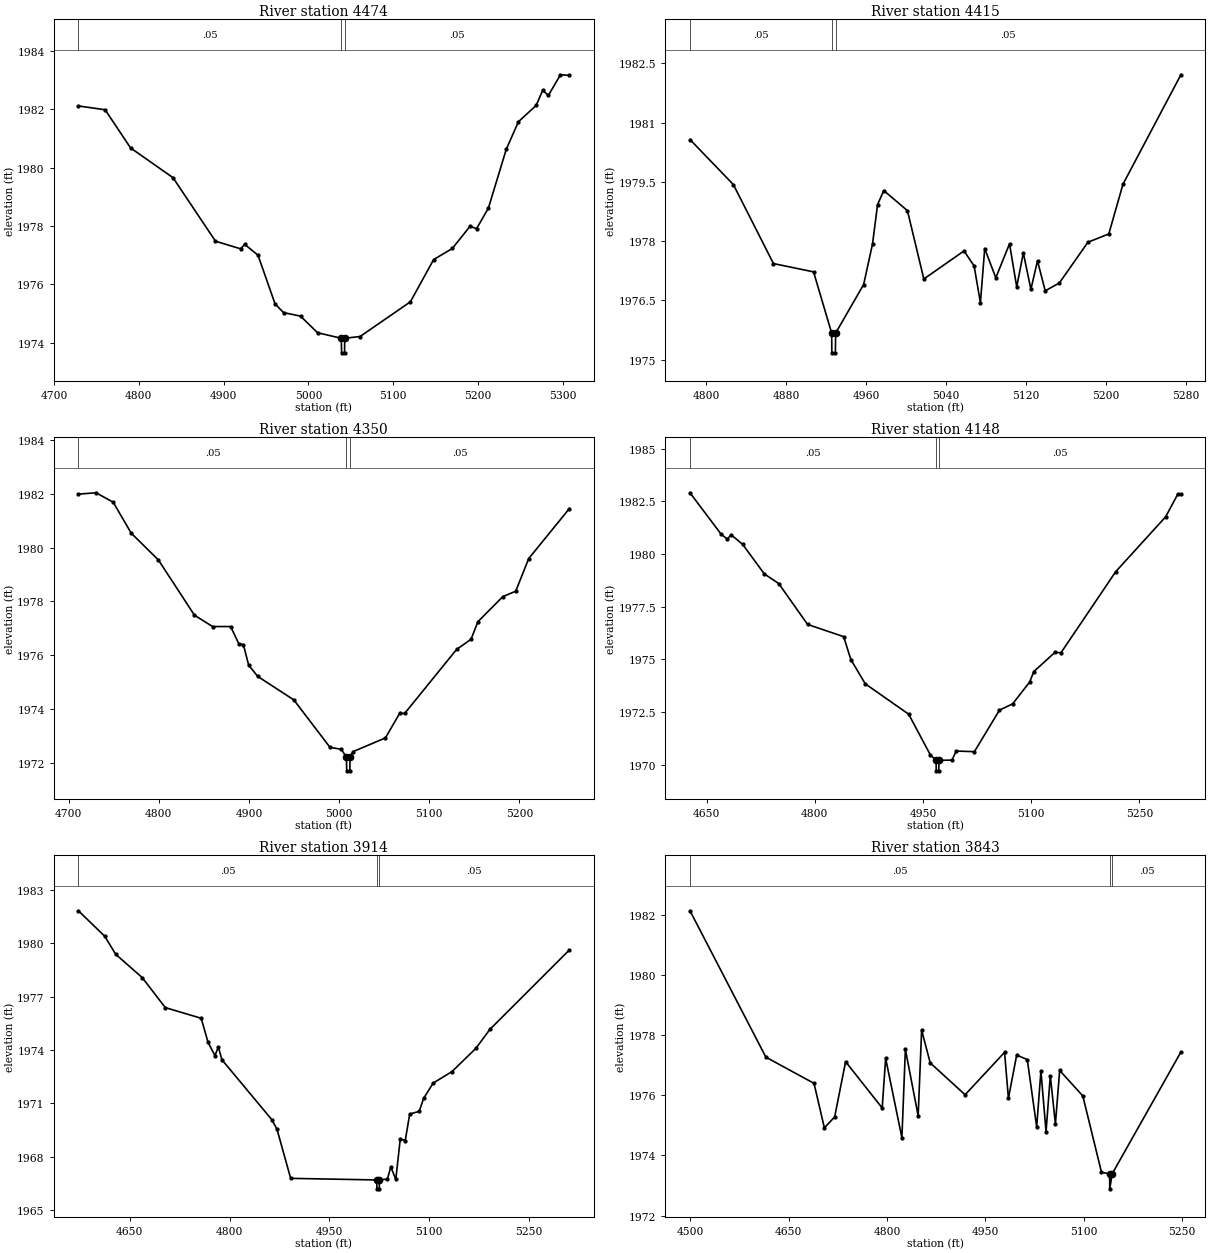
Type RM Length L Ch R = 1,4474,59,59,59
BEGIN DESCRIPTION:
Elm 01 69 4377.525
END DESCRIPTION:
XS GIS Cut Line= 5
      1570283.53      6767121.09      1570377.27      6767119.36
      1570554.36      6767108.26      1570634.39      6767102.87
      1570807.85      6766956.14
#Sta/Elev= 30
  4728.8 1982.12  4760.3 1981.99  4790.3 1980.68  4840.3 1979.66  4890.4 1977.48
  4919.9 1977.22  4924.9 1977.37  4940.5 1977.00  4960.6 1975.33  4970.6 1975.03
  4990.6 1974.91  5010.7 1974.34  5038.7 1974.15  5039.0 1973.65  5042.5 1973.65
  5042.7 1974.15  5060.8 1974.21  5120.1 1975.40  5147.5 1976.85  5169.5 1977.23
  5190.4 1977.99  5198.1 1977.91  5212.0 1978.61  5233.2 1980.64  5247.5 1981.58
  5268.4 1982.14  5276.1 1982.66  5282.7 1982.48  5297.0 1983.19  5307.4 1983.17
#Mann=3,-1,0
  4728.8    0.05       0  5038.7    0.03       0  5042.7    0.05       0
Bank Sta=5038.7,5042.7
Exp/Cntr=0.3,0.1

Type RM Length L Ch R = 1,4415,65,65,65
BEGIN DESCRIPTION:
Elm 01 69 4414.74
END DESCRIPTION:
XS GIS Cut Line= 4
      1570361.64      6767174.91      1570578.66      6767161.03
      1570658.52      6767152.34      1570804.35      6767025.61
#Sta/Elev= 30
  4784.0 1980.57  4827.4 1979.43  4867.5 1977.43  4907.6 1977.22  4925.7 1975.67
  4925.9 1975.17  4929.4 1975.17  4929.7 1975.67  4957.7 1976.90  4966.6 1977.93
  4971.6 1978.92  4977.8 1979.28  5001.5 1978.77  5017.9 1977.04  5058.1 1977.75
  5068.2 1977.37  5074.5 1976.44  5078.8 1977.81  5089.9 1977.07  5103.6 1977.93
  5110.8 1976.84  5117.4 1977.70  5125.0 1976.78  5131.6 1977.50  5139.3 1976.74
  5153.5 1976.94  5182.0 1977.97  5202.9 1978.18  5217.1 1979.44  5275.0 1982.21
#Mann=3,-1,0
  4784.0    0.05       0  4925.7    0.05       0  4929.7    0.05       0
Bank Sta=4925.7,4929.7
Exp/Cntr=0.3,0.1

Type RM Length L Ch R = 1,4350,202,202,202
BEGIN DESCRIPTION:
Elm 01 69 4350.26
END DESCRIPTION:
XS GIS Cut Line= 5
      1570316.49      6767233.94      1570604.70      6767216.58
      1570670.67      6767200.96      1570727.96      6767171.44
      1570823.41      6767093.35
#Sta/Elev= 30
  4710.9 1981.98  4730.5 1982.03  4749.5 1981.68  4769.5 1980.53  4799.6 1979.54
  4839.6 1977.49  4859.7 1977.07  4879.7 1977.07  4888.8 1976.43  4893.8 1976.40
  4899.7 1975.64  4909.8 1975.22  4949.8 1974.35  4989.9 1972.59  5002.4 1972.52
  5008.1 1972.22  5008.4 1971.72  5011.9 1971.72  5012.1 1972.22  5015.3 1972.43
  5051.3 1972.94  5067.1 1973.85  5072.7 1973.85  5130.2 1976.22  5146.3 1976.60
  5153.9 1977.25  5181.5 1978.18  5195.8 1978.38  5210.2 1979.59  5255.2 1981.44
#Mann=3,-1,0
  4710.9    0.05       0  5008.1    0.05       0  5012.1    0.05       0
Bank Sta=5008.1,5012.1
Exp/Cntr=0.3,0.1

Type RM Length L Ch R = 1,4148,234,234,234
BEGIN DESCRIPTION:
Elm 01 69 4148.28
END DESCRIPTION:
XS GIS Cut Line= 3
      1570282.05      6767414.57      1570651.81      6767404.15
      1570938.26      6767284.36
#Sta/Elev= 30
  4627.0 1982.90  4670.0 1980.94  4678.8 1980.70  4683.9 1980.91  4700.0 1980.45
  4730.0 1979.05  4750.0 1978.59  4790.0 1976.65  4840.0 1976.07  4850.0 1974.98
  4870.0 1973.83  4930.1 1972.39  4960.1 1970.46  4968.1 1970.20  4968.3 1969.70
  4971.8 1969.70  4972.1 1970.20  4990.1 1970.21  4996.0 1970.64  5021.2 1970.61
  5055.9 1972.58  5074.2 1972.88  5097.9 1973.92  5103.5 1974.41  5132.7 1975.32
  5141.3 1975.31  5217.2 1979.16  5286.3 1981.76  5302.9 1982.82  5307.4 1982.82
#Mann=3,-1,0
  4627.0    0.05       0  4968.1    0.05       0  4972.1    0.05       0
Bank Sta=4968.1,4972.1
Exp/Cntr=0.3,0.1

Type RM Length L Ch R = 1,3914,71,71,71
BEGIN DESCRIPTION:
Mapping XS 7a8458e3
END DESCRIPTION:
XS GIS Cut Line= 5
      1570316.86      6767528.09      1570581.64      6767599.71
      1570659.76      6767619.24      1570766.10      6767610.56
      1570950.26      6767404.74
#Sta/Elev= 30
  4572.7 1981.83  4612.2 1980.40  4628.8 1979.38  4668.6 1978.07  4703.3 1976.38
  4757.2 1975.78  4767.6 1974.42  4777.9 1973.68  4783.1 1974.16  4788.3 1973.45
  4863.2 1970.08  4871.1 1969.54  4891.7 1966.77  5021.1 1966.68  5021.3 1966.18
  5024.8 1966.18  5025.1 1966.68  5037.1 1966.73  5042.2 1967.42  5049.7 1966.71
  5056.4 1968.99  5063.9 1968.90  5070.6 1970.39  5084.8 1970.54  5091.5 1971.27
  5105.8 1972.13  5134.2 1972.78  5170.1 1974.09  5191.0 1975.15  5310.4 1979.62
#Mann=3,-1,0
  4572.7    0.05       0  5021.1    0.05       0  5025.1    0.05       0
Bank Sta=5021.1,5025.1
Exp/Cntr=0.3,0.1

Type RM Length L Ch R = 1,3843,104,104,104
BEGIN DESCRIPTION:
Elm 01 69 3843.15
END DESCRIPTION:
XS GIS Cut Line= 6
      1570304.53      6767561.34      1570545.38      6767637.28
      1570653.89      6767678.52      1570760.23      6767678.52
      1570779.76      6767665.50      1570940.11      6767473.08
#Sta/Elev= 30
  4499.3 1982.14  4615.1 1977.27  4688.5 1976.40  4704.3 1974.92  4720.0 1975.28
  4736.7 1977.12  4792.5 1975.58  4797.8 1977.23  4822.6 1974.59  4827.9 1977.53
  4847.4 1975.32  4852.7 1978.17  4865.8 1977.08  4919.0 1976.02  4979.2 1977.43
  4985.1 1975.90  4997.7 1977.34  5013.9 1977.19  5028.2 1974.95  5034.7 1976.81
  5042.5 1974.79  5049.0 1976.65  5056.8 1975.05  5063.3 1976.83  5098.6 1975.98
  5127.1 1973.44  5139.4 1973.39  5139.7 1972.89  5143.4 1973.39  5248.2 1977.44
#Mann=3,-1,0
  4499.3    0.05       0  5139.4    0.05       0  5143.4    0.05       0
Bank Sta=5139.4,5143.4
Exp/Cntr=0.3,0.1

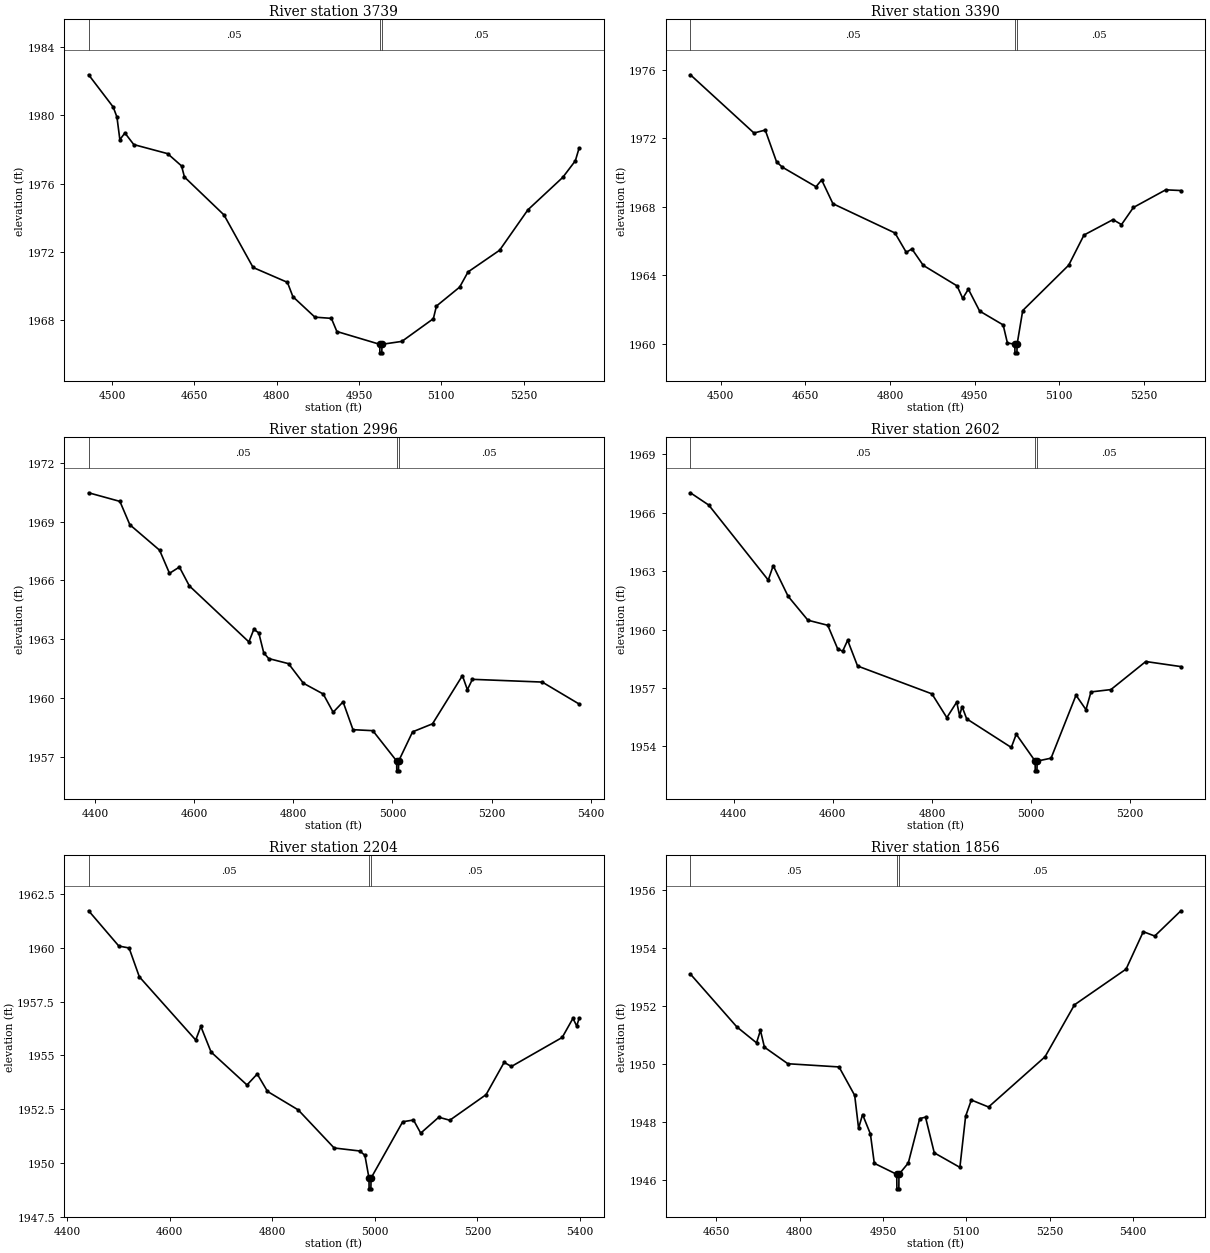
Type RM Length L Ch R = 1,3739,349,349,349
BEGIN DESCRIPTION:
Elm 01 69 3738.55
END DESCRIPTION:
XS GIS Cut Line= 5
      1570282.81      6767635.12      1570603.98      6767750.13
      1570805.80      6767760.98      1570883.93      6767739.28
      1571028.82      6767512.21
#Sta/Elev= 30
  4457.5 1982.37  4502.3 1980.48  4509.1 1979.89  4514.4 1978.57  4523.6 1978.96
  4539.8 1978.28  4601.4 1977.75  4626.8 1977.03  4632.1 1976.38  4704.1 1974.16
  4757.2 1971.08  4819.7 1970.21  4829.7 1969.37  4869.8 1968.17  4899.8 1968.10
  4909.8 1967.33  4987.9 1966.58  4988.2 1966.08  4991.7 1966.08  4991.9 1966.58
  5028.2 1966.75  5085.6 1968.08  5091.2 1968.82  5133.5 1969.93  5148.8 1970.82
  5206.3 1972.09  5257.9 1974.46  5321.4 1976.36  5344.3 1977.33  5351.2 1978.08
#Mann=3,-1,0
  4457.5    0.05       0  4987.9    0.05       0  4991.9    0.05       0
Bank Sta=4987.9,4991.9
Exp/Cntr=0.3,0.1

Type RM Length L Ch R = 1,3390,394,394,394
BEGIN DESCRIPTION:
Elm 01 69 3390.07
END DESCRIPTION:
XS GIS Cut Line= 3
      1570352.36      6768068.22      1570901.81      6768081.24
      1571170.05      6767906.75
#Sta/Elev= 30
  4446.0 1975.71  4558.7 1972.31  4578.7 1972.48  4598.7 1970.63  4608.7 1970.32
  4668.7 1969.17  4678.7 1969.57  4698.7 1968.18  4808.7 1966.47  4828.7 1965.34
  4838.7 1965.54  4858.8 1964.58  4918.8 1963.38  4928.8 1962.65  4938.8 1963.19
  4958.8 1961.91  5000.5 1961.10  5008.0 1960.05  5021.2 1959.97  5021.4 1959.47
  5024.9 1959.47  5025.2 1959.97  5035.2 1961.94  5116.7 1964.59  5143.8 1966.35
  5195.2 1967.25  5210.3 1966.96  5231.4 1967.96  5288.7 1968.99  5315.6 1968.95
#Mann=3,-1,0
  4446.0    0.05       0  5021.2    0.05       0  5025.2    0.05       0
Bank Sta=5021.2,5025.2
Exp/Cntr=0.3,0.1

Type RM Length L Ch R = 1,2996,394,394,394
BEGIN DESCRIPTION:
Elm 01 69 2995.85
END DESCRIPTION:
XS GIS Cut Line= 3
      1570291.87      6768450.88      1570901.66      6768442.20
      1571279.31      6768405.31
#Sta/Elev= 30
  4387.2 1970.47  4450.3 1970.03  4470.3 1968.84  4530.3 1967.54  4550.3 1966.36
  4570.3 1966.68  4590.3 1965.72  4710.4 1962.86  4720.4 1963.50  4730.4 1963.32
  4740.4 1962.30  4750.4 1962.01  4790.4 1961.75  4820.4 1960.75  4860.4 1960.20
  4880.4 1959.27  4900.4 1959.80  4920.4 1958.38  4960.4 1958.33  5008.5 1956.78
  5008.7 1956.28  5012.2 1956.28  5012.5 1956.78  5040.6 1958.27  5080.8 1958.68
  5141.1 1961.14  5151.1 1960.42  5161.2 1960.95  5302.1 1960.81  5376.5 1959.69
#Mann=3,-1,0
  4387.2    0.05       0  5008.5    0.03       0  5012.5    0.05       0
Bank Sta=5008.5,5012.5
Exp/Cntr=0.3,0.1

Type RM Length L Ch R = 1,2602,398,398,398
BEGIN DESCRIPTION:
Elm 01 69 2602.43
END DESCRIPTION:
XS GIS Cut Line= 3
      1570268.03      6768835.00      1570955.92      6768819.81
      1571255.42      6768789.42
#Sta/Elev= 30
  4313.0 1967.02  4350.0 1966.39  4470.0 1962.54  4480.0 1963.28  4510.0 1961.71
  4550.0 1960.48  4590.0 1960.22  4610.0 1959.01  4620.0 1958.89  4630.1 1959.45
  4650.1 1958.13  4800.1 1956.70  4830.1 1955.48  4850.1 1956.28  4855.8 1955.58
  4860.8 1956.05  4870.1 1955.42  4960.1 1953.95  4970.1 1954.63  5008.2 1953.25
  5008.4 1952.75  5011.9 1952.75  5012.2 1953.25  5040.3 1953.40  5090.6 1956.63
  5110.7 1955.89  5120.8 1956.80  5161.0 1956.92  5231.3 1958.36  5302.1 1958.10
#Mann=3,-1,0
  4313.0    0.05       0  5008.2    0.05       0  5012.2    0.05       0
Bank Sta=5008.2,5012.2
Exp/Cntr=0.3,0.1

Type RM Length L Ch R = 1,2204,348,348,348
BEGIN DESCRIPTION:
Elm 01 69 2203.83
END DESCRIPTION:
XS GIS Cut Line= 3
      1570446.13      6769197.73      1571006.87      6769202.94
      1571295.42      6768931.67
#Sta/Elev= 30
  4441.6 1961.72  4500.5 1960.08  4520.5 1959.99  4540.5 1958.65  4650.5 1955.71
  4660.5 1956.34  4680.5 1955.15  4750.5 1953.62  4770.5 1954.13  4790.5 1953.32
  4850.5 1952.46  4920.5 1950.69  4970.5 1950.55  4980.5 1950.35  4988.5 1949.29
  4988.7 1948.79  4992.2 1948.79  4992.5 1949.29  5054.3 1951.91  5075.3 1951.99
  5089.4 1951.38  5124.6 1952.12  5146.1 1951.98  5216.9 1953.17  5252.1 1954.67
  5266.3 1954.48  5365.4 1955.83  5386.4 1956.72  5393.7 1956.36  5398.4 1956.72
#Mann=3,-1,0
  4441.6    0.05       0  4988.5    0.03       0  4992.5    0.05       0
Bank Sta=4988.5,4992.5
Exp/Cntr=0.3,0.1

Type RM Length L Ch R = 1,1856,402,402,402
BEGIN DESCRIPTION:
Elm 01 69 1950.66
END DESCRIPTION:
XS GIS Cut Line= 3
      1570872.47      6769763.74      1571134.59      6769492.94
      1571259.40      6769002.36
#Sta/Elev= 30
  4603.3 1953.10  4686.9 1951.28  4722.4 1950.73  4729.4 1951.16  4736.6 1950.58
  4778.8 1950.01  4870.9 1949.90  4899.1 1948.92  4906.1 1947.79  4913.3 1948.26
  4927.4 1947.59  4934.4 1946.58  4974.8 1946.20  4975.1 1945.70  4978.6 1945.70
  4978.8 1946.20  4995.6 1946.59  5016.2 1948.12  5026.6 1948.17  5042.4 1946.94
  5088.5 1946.44  5098.8 1948.20  5109.1 1948.76  5140.1 1948.52  5241.8 1950.25
  5294.8 1952.04  5387.7 1953.27  5418.7 1954.56  5439.3 1954.41  5486.4 1955.28
#Mann=3,-1,0
  4603.3    0.05       0  4974.8    0.05       0  4978.8    0.05       0
Bank Sta=4974.8,4978.8
Exp/Cntr=0.3,0.1

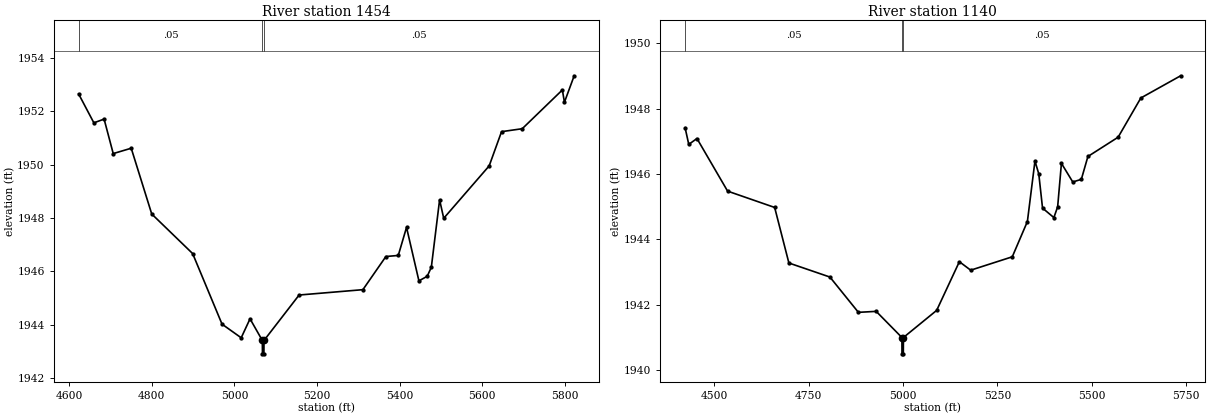
Type RM Length L Ch R = 1,1454,314,314,314
BEGIN DESCRIPTION:
Elm 01 69 1495.07
END DESCRIPTION:
XS GIS Cut Line= 3
      1570936.64      6769956.50      1571349.87      6769800.23
      1571381.09      6769042.27
#Sta/Elev= 30
  4622.6 1952.64  4659.5 1951.56  4684.3 1951.70  4706.4 1950.41  4750.0 1950.61
  4799.7 1948.15  4898.8 1946.67  4970.0 1944.03  5016.4 1943.52  5037.8 1944.23
  5067.6 1943.42  5067.9 1942.92  5071.4 1942.92  5071.6 1943.42  5156.7 1945.12
  5311.2 1945.32  5366.9 1946.56  5396.9 1946.60  5416.9 1947.65  5446.9 1945.65
  5467.0 1945.82  5477.0 1946.16  5497.0 1948.68  5507.0 1947.99  5617.1 1949.95
  5647.1 1951.23  5697.2 1951.34  5794.4 1952.79  5799.4 1952.33  5823.0 1953.32
#Mann=3,-1,0
  4622.6    0.05       0  5067.6    0.05       0  5071.6    0.05       0
Bank Sta=5067.6,5071.6
Exp/Cntr=0.3,0.1

Type RM Length L Ch R = 1,1140,0,0,0
BEGIN DESCRIPTION:
Elm 01 69 3429.681
END DESCRIPTION:
XS GIS Cut Line= 3
      1571111.98      6770117.96      1571547.78      6769874.88
      1571580.76      6769062.67
#Sta/Elev= 30
  4423.0 1947.42  4432.7 1946.91  4454.4 1947.09  4535.5 1945.48  4660.1 1944.98
  4697.8 1943.28  4806.4 1942.85  4881.8 1941.77  4928.9 1941.80  4997.0 1941.00
  4997.2 1940.50  5000.7 1940.50  5001.0 1941.00  5089.0 1941.83  5149.1 1943.32
  5179.1 1943.06  5289.2 1943.47  5329.2 1944.55  5349.2 1946.40  5359.3 1946.01
  5369.3 1944.96  5399.3 1944.67  5409.3 1945.00  5419.3 1946.33  5449.3 1945.76
  5472.0 1945.84  5489.4 1946.54  5569.4 1947.13  5629.5 1948.33  5734.9 1949.01
#Mann=3,-1,0
  4423.0    0.05       0  4997.0    0.05       0  5001.0    0.05       0
Bank Sta=4997,5001
Exp/Cntr=0.3,0.1

Chan Stop Cuts=-1