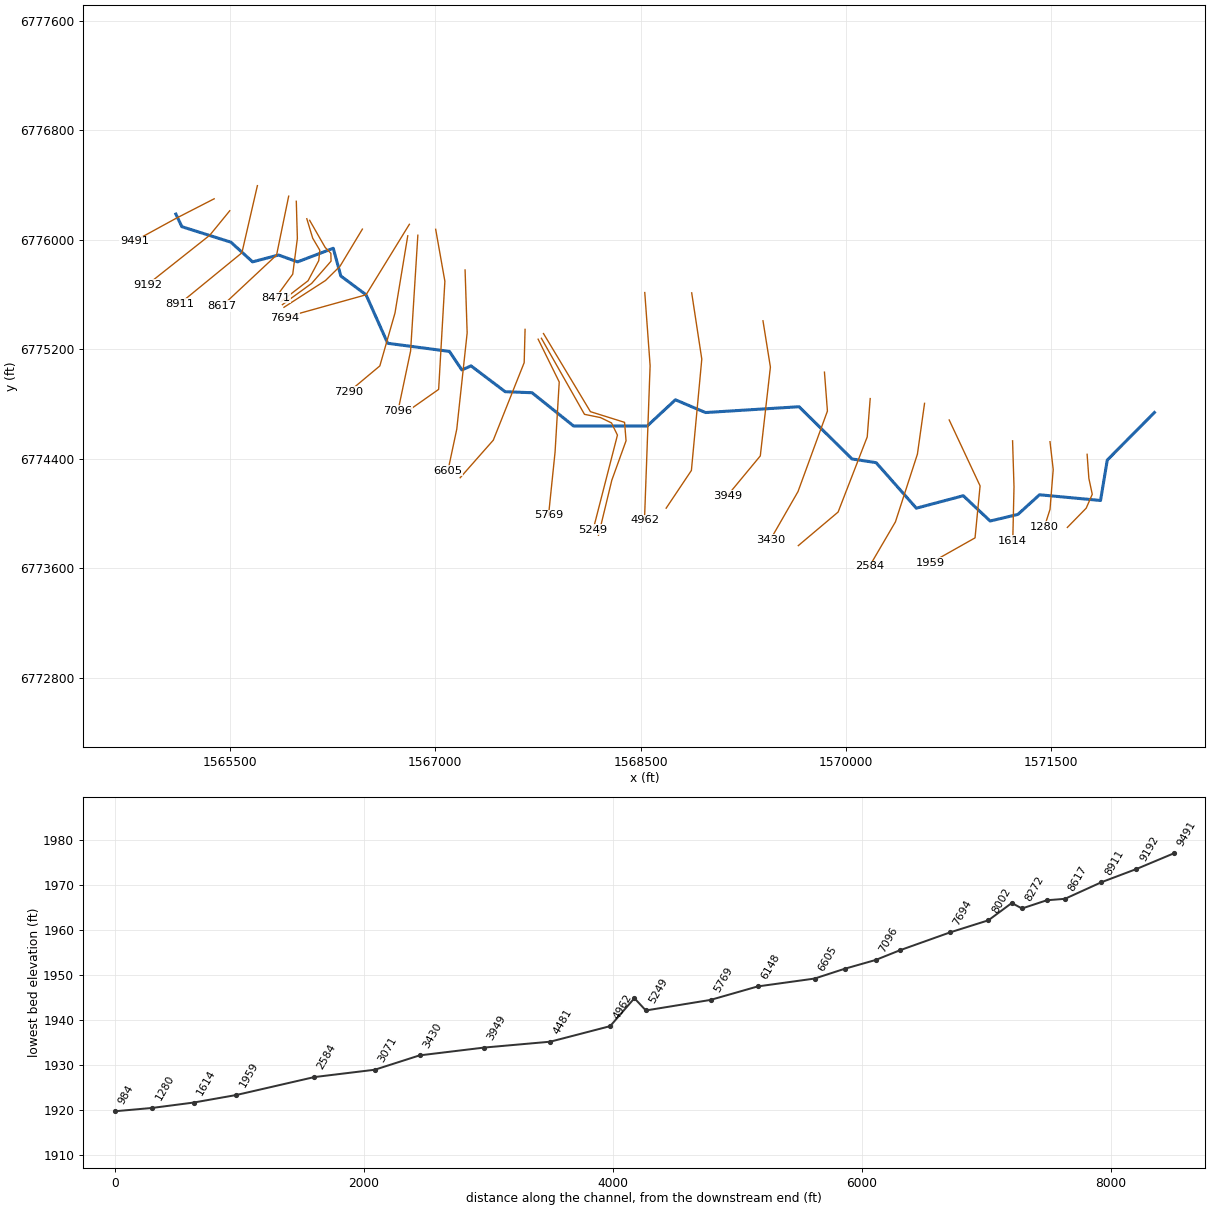
--- Elm 01 70.prj (project) ---

Proj Title=Elm 01 70 Base Level Engineering
Current Plan=p01
Default Exp/Contr=0.3,0.1
English Units
Geom File=g01
Flow File=f01
Plan File=p01
Y Axis Title=Elevation
X Axis Title(PF)=Main Channel Distance
X Axis Title(XS)=Station
BEGIN DESCRIPTION:
Elm 01 70
END DESCRIPTION:
DSS Export Rating Curves= 0
DSS Export Rating Curve Sorted= 0
DSS Export Volume Flow Curves= 0
DXF OffsetX= 0
DXF OffsetY= 0
DXF ScaleX= 1
DXF ScaleY= 10

--- Elm 01 70.p01 (plan) ---

Plan Title=Multiple Run
Short Identifier=Multiple
Geom File=g01
Flow File=f01
Subcritical Flow
K Sum by GR= 0
Std Step Tol= 0.01
Critical Tol= 0.01
Num of Std Step Trials= 20
Max Error Tol= 0.3
Flow Tol Ratio= 0.001
Split Flow NTrial= 30
Split Flow Tol= 0.02
Split Flow Ratio= 0.02
Log Output Level= 0
Friction Slope Method= 1
Unsteady Friction Slope Method= 2
Unsteady Bridges Friction Slope Method= 1
Parabolic Critical Depth
Global Vel Dist=  1 , 1 , 1
Global Log Level= 0
CheckData=True
Encroach Param= -1, 0, 0, 0
BEGIN DESCRIPTION:
Multiple Run
END DESCRIPTION:

--- Elm 01 70.f01 (steady flow) ---

Flow Title=Multiple
Number of Profiles=7
Profile Names=10-year,25-year,50-year,1pct_min,100-year,1pct_plu,500-year
River Rch & RM= Elm 01 70,Reach-1,9491
      51      63      73      52      83     115     111
River Rch & RM= Elm 01 70,Reach-1,8002
      83     108     128      95     152     209     215
River Rch & RM= Elm 01 70,Reach-1,7290
     172     233     282     213     341     469     503
Boundary for River Rch & Prof#=Elm 01 70,Reach-1,1
Up Type=0
Dn Type=3
Dn Slope=0.001
Boundary for River Rch & Prof#=Elm 01 70,Reach-1,2
Up Type=0
Dn Type=3
Dn Slope=0.001
Boundary for River Rch & Prof#=Elm 01 70,Reach-1,3
Up Type=0
Dn Type=3
Dn Slope=0.001
Boundary for River Rch & Prof#=Elm 01 70,Reach-1,4
Up Type=0
Dn Type=3
Dn Slope=0.001
Boundary for River Rch & Prof#=Elm 01 70,Reach-1,5
Up Type=0
Dn Type=3
Dn Slope=0.001
Boundary for River Rch & Prof#=Elm 01 70,Reach-1,6
Up Type=0
Dn Type=3
Dn Slope=0.001
Boundary for River Rch & Prof#=Elm 01 70,Reach-1,7
Up Type=0
Dn Type=3
Dn Slope=0.001

--- Elm 01 70.g01 (geometry) ---

Geom Title=Existing Conditions
Program Version=4.10

River Reach=Elm 01 70       ,Reach-1
Reach XY= 30
        1565105.        6776188.      1565148.69      6776095.95
      1565507.43      6775982.48      1565665.48      6775838.93
        1565855.      6775888.81      1565994.31      6775838.77
        1566255.        6775938.      1566310.46      6775735.54
      1566494.71      6775598.18      1566652.69      6775243.82
      1567103.75      6775184.54      1567194.69      6775049.12
      1567261.92      6775078.77      1567510.93      6774890.24
      1567707.45      6774882.53      1568011.03      6774639.62
      1568548.96      6774639.62        1568755.      6774830.91
      1568975.13      6774737.82      1569658.67      6774780.31
      1570045.32      6774398.75       1570221.7      6774371.63
      1570515.44      6774039.04      1570858.32      6774129.96
      1571054.69      6773945.23      1571257.45      6773993.47
      1571415.43      6774136.95      1571861.39      6774095.34
      1571910.45      6774390.47        1572255.        6774738.

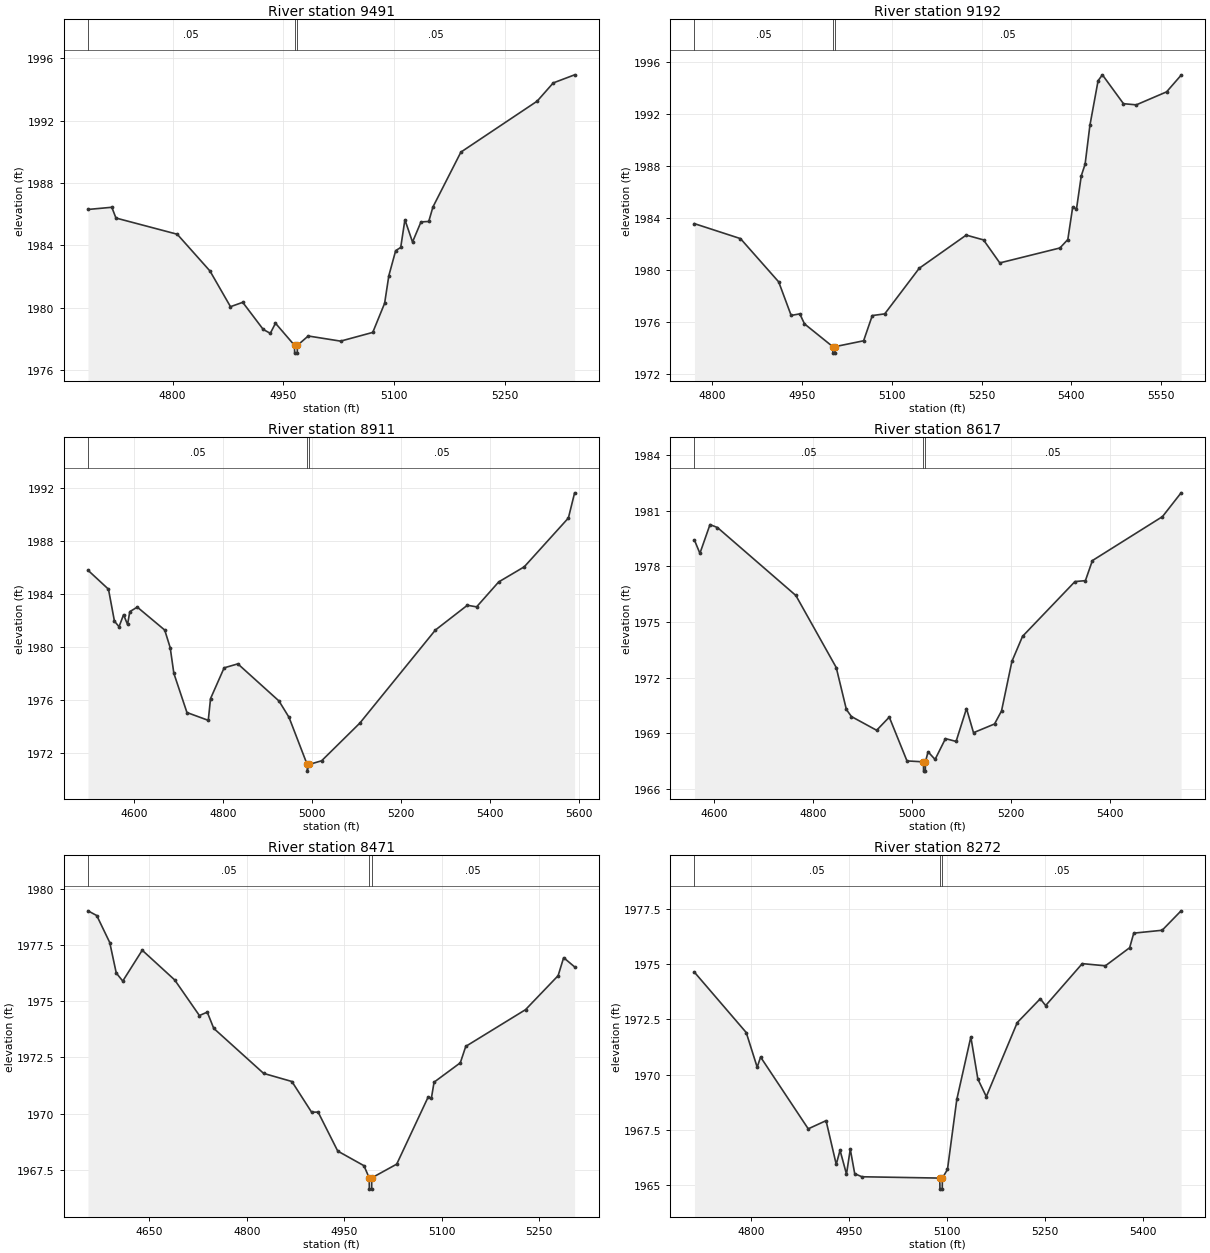
Type RM Length L Ch R = 1 ,9491    ,299,299,299
BEGIN DESCRIPTION:
Elm 01 70 9040.957
END DESCRIPTION:
XS GIS Cut Line= 3
      1565384.93      6776299.66      1565104.85      6776155.95
      1564802.18      6775990.38
#Sta/Elev= 30
  4685.2  1986.3  4717.5 1986.44  4723.1 1985.75  4806.2 1984.71  4850.6 1982.35
  4878.4 1980.06    4895 1980.34  4922.8  1978.6  4932.4 1978.35  4939.4    1979
  4965.2 1977.58  4965.4 1977.08  4968.9 1977.08  4969.2 1977.58  4983.8 1978.18
  5027.7 1977.85  5071.3 1978.41  5087.4 1980.28  5093.1 1982.05  5102.4 1983.66
  5109.2 1983.86  5114.9 1985.64  5125.2 1984.21  5136.7  1985.5  5147.2 1985.53
  5152.9 1986.46  5190.8 1989.98  5294.2 1993.25    5316 1994.42    5345 1994.94
#Mann= 3 ,-1 , 0
  4685.2     .05       0  4965.2     .03       0  4969.2     .05       0
Bank Sta=4965.2,4969.2
XS Rating Curve= 0 ,0
Exp/Cntr=0.3,0.1

Type RM Length L Ch R = 1 ,9192    ,281,281,281
BEGIN DESCRIPTION:
Elm 01 70 9192.45
END DESCRIPTION:
XS GIS Cut Line= 3
      1565498.94      6776212.22      1565353.14      6776033.87
       1564896.3      6775671.77
#Sta/Elev= 30
    4770 1983.57  4846.9 1982.42  4910.8 1979.09  4931.6 1976.51    4946 1976.63
  4953.9 1975.86  5001.1 1974.11  5001.3 1973.61  5004.8 1973.61  5005.1 1974.11
  5052.7 1974.56  5067.2  1976.5    5088 1976.63  5145.7 1980.14  5224.2 1982.69
  5253.1 1982.32  5280.3 1980.55  5380.8  1981.7    5394 1982.35  5402.1 1984.83
  5408.5  1984.7  5416.5 1987.25  5422.9 1988.15  5430.9 1991.13  5444.6 1994.57
  5451.8 1995.02    5487  1992.8  5508.4 1992.71  5559.1 1993.71  5583.3 1994.99
#Mann= 3 ,-1 , 0
    4770     .05       0  5001.1     .03       0  5005.1     .05       0
Bank Sta=5001.1,5005.1
XS Rating Curve= 0 ,0
Exp/Cntr=0.3,0.1

Type RM Length L Ch R = 1 ,8911    ,294,294,294
BEGIN DESCRIPTION:
Elm 01 70 8911.33
END DESCRIPTION:
XS GIS Cut Line= 3
       1565700.8      6776395.89      1565587.51      6775904.96
      1565131.56      6775532.14
#Sta/Elev= 30
  4496.7 1985.82  4542.7 1984.39  4556.1 1981.98  4566.4 1981.56  4576.6 1982.47
  4585.5 1981.73  4590.6  1982.7  4607.4 1983.04    4669 1981.31  4681.3 1979.98
  4689.5 1978.05  4718.9 1975.09  4766.8  1974.5  4771.9 1976.14  4802.4 1978.46
  4833.2 1978.76  4925.6 1975.96  4948.1 1974.73  4988.9 1971.17  4989.1 1970.67
  4992.9 1971.17  5021.3 1971.45  5107.1 1974.29  5276.8 1981.31  5348.6 1983.18
  5369.4 1983.06    5419 1984.94  5476.4 1986.08  5575.5 1989.76  5589.5 1991.66
#Mann= 3 ,-1 , 0
  4496.7     .05       0  4988.9     .05       0  4992.9     .05       0
Bank Sta=4988.9,4992.9
XS Rating Curve= 0 ,0
Exp/Cntr=0.3,0.1

Type RM Length L Ch R = 1 ,8617    ,146,146,146
BEGIN DESCRIPTION:
Elm 01 70 8616.58
END DESCRIPTION:
XS GIS Cut Line= 3
       1565929.3      6776318.77      1565840.77      6775888.25
      1565443.18       6775516.7
#Sta/Elev= 30
  4560.7 1979.41  4571.7  1978.7  4592.1 1980.25  4607.2 1980.09  4765.7 1976.43
  4847.3 1972.55  4867.8 1970.29    4878 1969.91    4929 1969.17  4954.5 1969.88
  4990.3 1967.52  5023.6 1967.47  5023.9 1966.97  5027.4 1966.97  5027.6 1967.47
  5032.9 1968.01  5047.1  1967.6  5068.1 1968.72  5089.6 1968.57  5110.6 1970.34
  5124.8 1969.04  5167.3 1969.51  5181.4 1970.21  5202.4 1972.88  5223.9 1974.23
  5329.9 1977.18    5351 1977.23  5365.1 1978.31  5506.8 1980.68  5544.4 1981.96
#Mann= 3 ,-1 , 0
  4560.7     .05       0  5023.6     .05       0  5027.6     .05       0
Bank Sta=5023.6,5027.6
XS Rating Curve= 0 ,0
Exp/Cntr=0.3,0.1

Type RM Length L Ch R = 1 ,8471    ,199,199,199
BEGIN DESCRIPTION:
Mapping XS 47c515c0
END DESCRIPTION:
XS GIS Cut Line= 4
        1565985.      6776281.48      1565992.81      6776009.38
      1565958.95      6775748.96      1565832.63      6775575.75
#Sta/Elev= 30
  4555.6 1979.01  4569.1  1978.8  4589.1  1977.6  4599.1 1976.25  4609.1 1975.89
  4639.1 1977.26  4689.1 1975.94  4727.1 1974.36  4739.2 1974.51  4749.2 1973.79
    4826 1971.79  4869.5 1971.43  4899.8 1970.07  4909.9 1970.07  4940.1 1968.34
  4980.5 1967.69  4988.5 1967.15  4988.8 1966.65  4992.3 1966.65  4992.5 1967.15
  5030.9 1967.76  5079.3 1970.74  5084.3 1970.69  5088.4  1971.4  5128.8 1972.26
  5137.2 1972.99  5229.2 1974.62  5279.4 1976.13  5287.9 1976.93  5304.8 1976.52
#Mann= 3 ,-1 , 0
  4555.6     .05       0  4988.5     .04       0  4992.5     .05       0
Bank Sta=4988.5,4992.5
XS Rating Curve= 0 ,0
Exp/Cntr=0.3,0.1

Type RM Length L Ch R = 1 ,8272    ,82,82,82
BEGIN DESCRIPTION:
Mapping XS c7ec3573
END DESCRIPTION:
XS GIS Cut Line= 6
      1566061.82      6776153.91      1566104.79      6776011.98
      1566156.87      6775923.44      1566149.06      6775847.92
      1566070.93      6775700.78      1565872.99      6775548.42
#Sta/Elev= 30
  4713.3 1974.64  4792.6 1971.91  4809.4 1970.34  4814.6  1970.8  4887.6 1967.55
  4914.9 1967.92  4930.5 1965.94  4936.3 1966.58  4946.2  1965.5    4952 1966.63
  4958.8 1965.52  4969.8 1965.38  5089.1 1965.32  5089.4 1964.82  5092.9 1964.82
  5093.1 1965.32  5100.9 1965.71  5115.2 1968.88  5136.7 1971.71  5147.5  1969.8
  5160.4 1969.01  5207.8 1972.36  5243.1 1973.44  5251.3 1973.13  5307.4 1975.03
  5342.8 1974.93    5380 1975.75  5386.3 1976.41  5429.8 1976.54  5458.8 1977.42
#Mann= 3 ,-1 , 0
  4713.3     .05       0  5089.1     .05       0  5093.1     .05       0
Bank Sta=5089.1,5093.1
XS Rating Curve= 0 ,0
Exp/Cntr=0.3,0.1

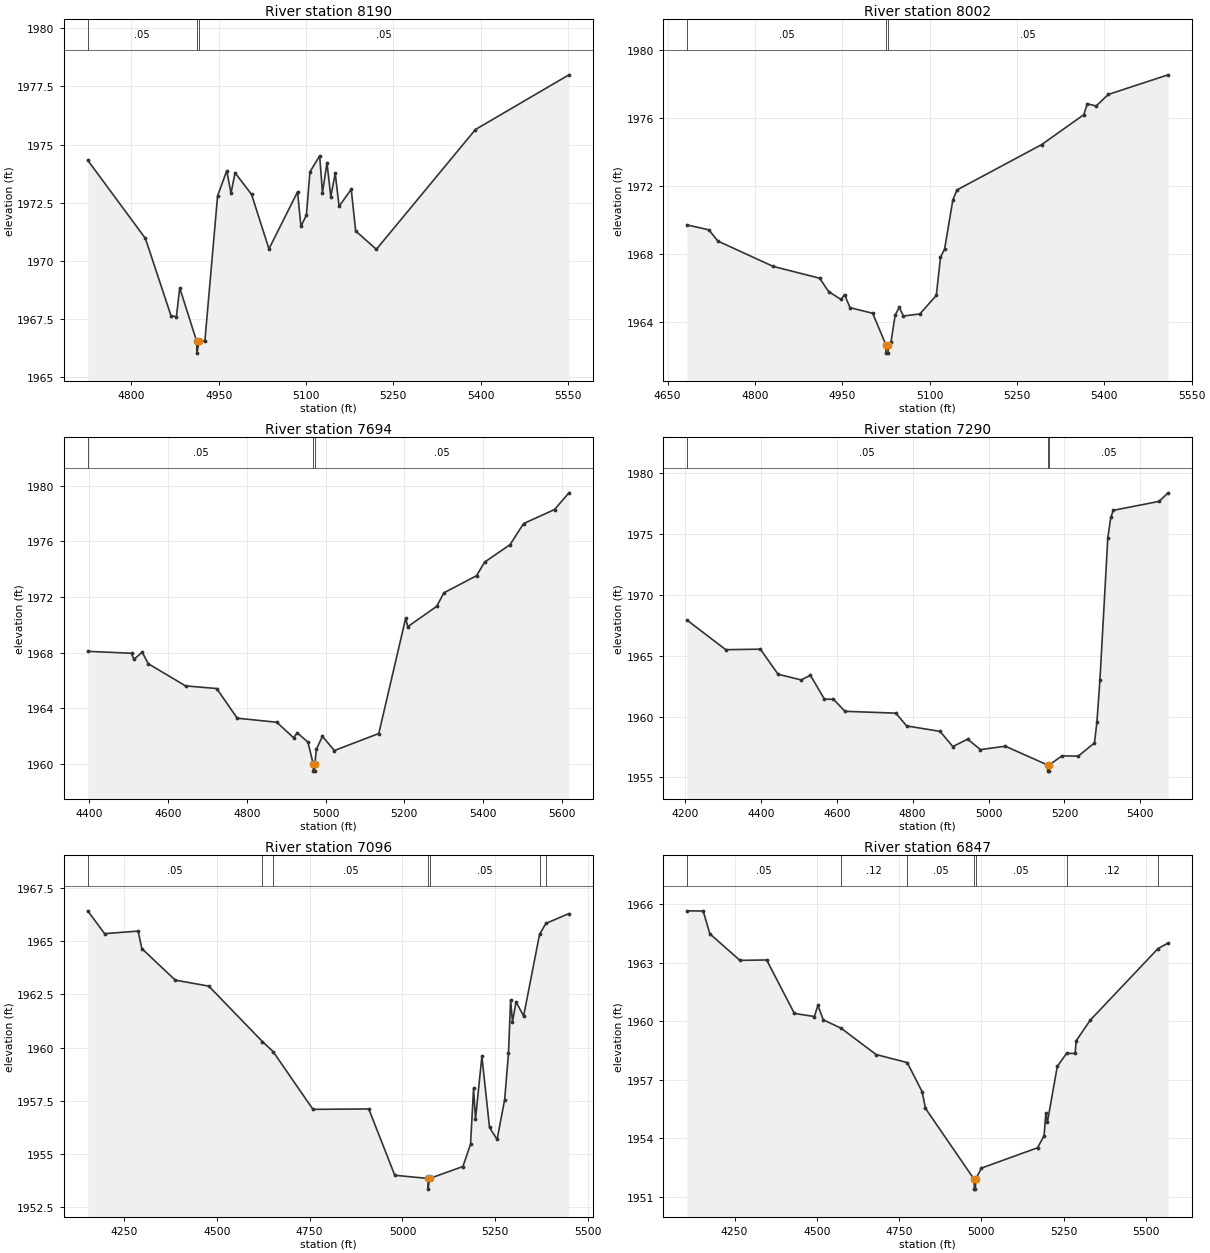
Type RM Length L Ch R = 1 ,8190    ,188,188,188
BEGIN DESCRIPTION:
Mapping XS 0d409101
END DESCRIPTION:
XS GIS Cut Line= 6
      1566082.65      6776142.18      1566195.93      6775944.27
       1566237.6       6775901.3       1566238.9      6775844.01
      1566096.97      6775681.25      1565883.41      6775526.28
#Sta/Elev= 30
  4725.2 1974.33  4824.2 1970.97  4868.3 1967.64  4877.5 1967.61  4883.2 1968.84
  4912.4 1966.54  4912.6 1966.04  4916.4 1966.54  4926.4 1966.57  4948.2  1972.8
    4964 1973.88  4971.2 1972.91  4978.2 1973.79  5006.5 1972.86  5036.4 1970.52
  5085.5 1972.97  5091.3 1971.49  5100.7 1971.97  5106.8 1973.83  5123.5 1974.52
  5128.3 1972.93    5136 1974.23  5142.6 1972.76  5150.2 1973.77  5156.8 1972.35
  5177.7 1973.08  5185.3 1971.29  5220.8  1970.5    5391 1975.65  5551.5    1978
#Mann= 3 ,-1 , 0
  4725.2     .05       0  4912.4     .05       0  4916.4     .05       0
Bank Sta=4912.4,4916.4
XS Rating Curve= 0 ,0
Exp/Cntr=0.3,0.1

Type RM Length L Ch R = 1 ,8002    ,308,308,308
BEGIN DESCRIPTION:
Elm 01 70 8002.19
END DESCRIPTION:
XS GIS Cut Line= 4
      1566467.82      6776077.96      1566304.64      6775807.16
      1566198.74      6775702.99       1565894.9      6775506.79
#Sta/Elev= 30
  4683.1 1969.72  4720.8 1969.43  4736.3 1968.77  4831.4 1967.28  4911.1 1966.59
  4926.6  1965.8  4947.9 1965.34  4953.8 1965.63  4963.3 1964.86  5002.2 1964.53
  5024.8 1962.69    5025 1962.19  5028.5 1962.19  5028.8 1962.69  5033.8 1962.87
  5040.8 1964.43  5047.9 1964.88  5054.9 1964.37  5083.2 1964.49  5111.5 1965.58
  5118.6 1967.81  5125.7  1968.3  5139.8 1971.17  5146.9 1971.77  5292.2 1974.43
  5364.8 1976.19  5370.7 1976.83  5385.9  1976.7    5407 1977.38  5509.5 1978.53
#Mann= 3 ,-1 , 0
  4683.1     .05       0  5024.8     .05       0  5028.8     .05       0
Bank Sta=5024.8,5028.8
XS Rating Curve= 0 ,0
Exp/Cntr=0.3,0.1

Type RM Length L Ch R = 1 ,7694    ,404,404,404
BEGIN DESCRIPTION:
Elm 01 70 7581.029
END DESCRIPTION:
XS GIS Cut Line= 3
      1566811.14      6776113.13      1566494.71      6775598.18
      1565898.73      6775432.06
#Sta/Elev= 30
  4395.6  1968.1  4506.9 1967.96  4512.8 1967.52    4534 1968.04  4549.5 1967.21
  4644.2 1965.62  4723.4 1965.43  4775.6  1963.3  4876.1 1963.01  4918.7  1961.9
  4928.3 1962.25  4955.4 1961.58  4968.8    1960  4969.1  1959.5  4972.6  1959.5
  4972.8    1960  4976.7 1961.06  4992.1    1962  5022.5 1960.98  5135.4  1962.2
  5203.8 1970.48    5209 1969.87  5282.6 1971.33  5300.8  1972.3  5383.8 1973.53
  5404.6 1974.51  5469.1 1975.76  5503.3 1977.27  5582.1 1978.28  5618.7 1979.48
#Mann= 3 ,-1 , 0
  4395.6     .05       0  4968.8     .05       0  4972.8     .05       0
Bank Sta=4968.8,4972.8
XS Rating Curve= 0 ,0
Exp/Cntr=0.3,0.1

Type RM Length L Ch R = 1 ,7290    ,194,194,194
BEGIN DESCRIPTION:
Mapping XS ffd8e2bc
END DESCRIPTION:
XS GIS Cut Line= 4
      1566799.37      6776029.04      1566706.06      6775464.82
      1566595.38      6775078.53      1566369.82      6774889.84
#Sta/Elev= 30
  4205.3 1967.94  4307.7  1965.5  4398.9 1965.54  4445.6 1963.48  4506.6 1963.01
  4530.7  1963.4  4567.7 1961.43  4591.5 1961.42  4621.9 1960.43  4755.9 1960.28
  4784.3 1959.23  4872.3 1958.78    4906 1957.53    4945 1958.14  4978.7 1957.28
  5044.3 1957.56  5155.9 1956.01  5156.2 1955.51  5159.7 1955.51  5159.9 1956.01
  5193.4 1956.77  5236.3 1956.74  5279.2 1957.83  5285.7 1959.58  5293.5 1962.98
  5314.4 1974.72  5322.2 1976.38  5328.7 1976.96  5449.7  1977.7  5473.1  1978.4
#Mann= 3 ,-1 , 0
  4205.3     .05       0  5155.9     .05       0  5159.9     .05       0
Bank Sta=5155.9,5159.9
XS Rating Curve= 0 ,0
Exp/Cntr=0.3,0.1

Type RM Length L Ch R = 1 ,7096    ,249,249,249
BEGIN DESCRIPTION:
Elm 01 70 7095.822
END DESCRIPTION:
XS GIS Cut Line= 3
      1566873.16      6776033.39      1566820.09      6775187.35
      1566727.76      6774748.66
#Sta/Elev= 30
  4152.3 1966.41  4197.8 1965.34    4288 1965.46    4298 1964.64  4388.1 1963.16
  4478.3 1962.88  4622.7 1960.28  4651.6 1959.81  4758.9  1957.1  4909.2 1957.12
  4979.3 1954.01  5068.9 1953.86  5069.1 1953.36  5072.9 1953.86  5162.8 1954.42
  5183.3 1955.47  5191.5 1958.09  5196.6 1956.64  5213.9 1959.59  5234.4 1956.25
  5254.8 1955.69  5275.2 1957.56  5285.5 1959.72  5291.2 1962.24  5296.3 1961.21
  5305.9 1962.14  5326.3 1961.48  5369.2 1965.31  5386.3 1965.82  5448.3 1966.28
#Mann= 7 ,-1 , 0
  4152.3     .05       0  4622.7     .12       0  4651.6     .05       0
  5068.9     .05       0  5072.9     .05       0  5369.2     .12       0
  5386.3     .05       0
Bank Sta=5068.9,5072.9
XS Rating Curve= 0 ,0
Exp/Cntr=0.3,0.1

Type RM Length L Ch R = 1 ,6847    ,242,242,242
BEGIN DESCRIPTION:
Mapping XS 50302acb
END DESCRIPTION:
XS GIS Cut Line= 4
      1567003.36      6776076.82      1567070.64      6775697.02
      1567025.07      6774907.09       1566791.3      6774742.59
#Sta/Elev= 30
  4105.1 1965.67  4154.7 1965.66    4175 1964.49  4266.4 1963.13  4347.6 1963.15
  4431.9 1960.41  4492.8 1960.25  4503.4 1960.82  4519.9 1960.08  4574.1 1959.65
  4680.4  1958.3  4774.9 1957.89  4820.4 1956.39  4830.4 1955.54  4978.6  1951.9
  4978.9  1951.4  4982.4  1951.4  4982.6  1951.9  5000.7 1952.48    5171 1953.52
    5191 1954.14  5196.2 1955.28  5201.2 1954.85  5231.1 1957.69  5259.2 1958.36
  5285.2 1958.36  5288.7 1959.01  5331.1 1960.06    5537 1963.73  5567.9 1964.02
#Mann= 7 ,-1 , 0
  4105.1     .05       0  4574.1     .12       0  4774.9     .05       0
  4978.6     .05       0  4982.6     .05       0  5259.2     .12       0
    5537     .05       0
Bank Sta=4978.6,4982.6
XS Rating Curve= 0 ,0
Exp/Cntr=0.3,0.1

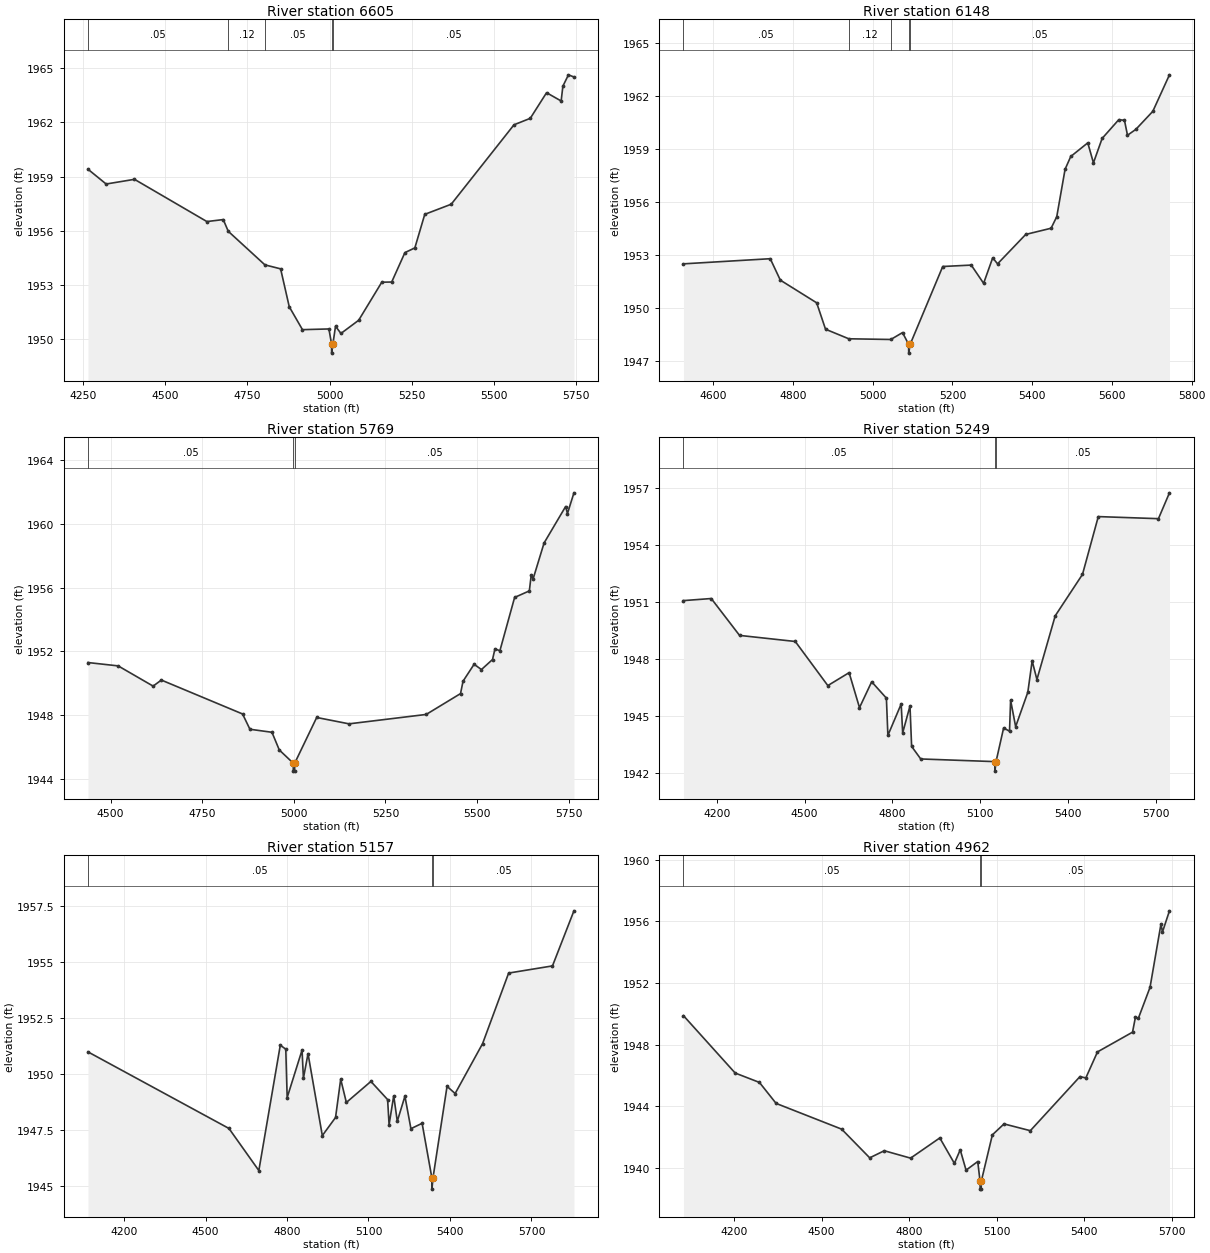
Type RM Length L Ch R = 1 ,6605    ,457,457,457
BEGIN DESCRIPTION:
Mapping XS 4780c857
END DESCRIPTION:
XS GIS Cut Line= 4
      1567218.21      6775779.48       1567233.4      6775319.42
      1567157.45      6774616.29      1567092.63      6774311.64
#Sta/Elev= 30
  4264.5 1959.41  4319.8 1958.59  4406.1 1958.85  4626.4 1956.51  4676.2 1956.62
  4691.5 1955.97    4803 1954.11  4850.8 1953.89  4877.1 1951.79  4917.3 1950.52
  4997.8 1950.56  5005.9 1949.72  5006.1 1949.22  5009.9 1949.72  5017.9 1950.71
  5034.4 1950.31  5088.3 1951.04  5158.7 1953.15  5188.9 1953.16  5229.1 1954.79
  5259.3 1955.05  5289.5 1956.91    5370 1957.47    5561 1961.87  5610.6 1962.23
  5660.2 1963.65  5704.6 1963.19  5709.8 1964.01  5726.8 1964.64  5743.5 1964.52
#Mann= 5 ,-1 , 0
  4264.5     .05       0  4691.5     .12       0    4803     .05       0
  5005.9     .05       0  5009.9     .05       0
Bank Sta=5005.9,5009.9
XS Rating Curve= 0 ,0
Exp/Cntr=0.3,0.1

Type RM Length L Ch R = 1 ,6148    ,379,379,379
BEGIN DESCRIPTION:
Mapping XS f4a4fa8b
END DESCRIPTION:
XS GIS Cut Line= 4
      1567656.58      6775345.49      1567650.07       6775102.4
      1567424.38        6774536.      1567182.49      6774261.71
#Sta/Elev= 30
  4525.7 1952.51  4743.3  1952.8  4768.6 1951.59  4859.7 1950.31  4881.9 1948.82
  4940.2 1948.28  5045.6 1948.24    5075 1948.63  5090.2 1947.97  5090.5 1947.47
  5094.2 1947.97  5175.8 1952.36  5247.3 1952.44  5278.3 1951.41  5301.1 1952.85
  5313.3 1952.51  5383.9 1954.17  5447.5 1954.52  5461.7 1955.17  5482.6 1957.85
  5496.8 1958.57  5539.5 1959.34  5553.7 1958.21  5575.5 1959.59  5617.3 1960.65
  5631.5 1960.61  5639.1 1959.77    5660  1960.1  5702.6 1961.12  5744.3 1963.18
#Mann= 5 ,-1 , 0
  4525.7     .05       0  4940.2     .12       0  5045.6     .05       0
  5090.2     .07       0  5094.2     .05       0
Bank Sta=5090.2,5094.2
XS Rating Curve= 0 ,0
Exp/Cntr=0.3,0.1

Type RM Length L Ch R = 1 ,5769    ,520,520,520
BEGIN DESCRIPTION:
Mapping XS dd245136
END DESCRIPTION:
XS GIS Cut Line= 4
      1567752.05      6775273.88      1567906.15      6774961.34
      1567875.76      6774449.19      1567828.02      6773986.97
#Sta/Elev= 30
  4438.3 1951.29  4520.7 1951.08  4616.1 1949.81  4638.6 1950.19  4860.2 1948.06
  4880.3  1947.1  4940.4 1946.91  4960.4  1945.8  4998.5 1944.97  4998.7 1944.47
  5002.2 1944.47  5002.5 1944.97  5062.5 1947.84  5150.7 1947.44  5361.3 1948.03
    5455 1949.34  5461.9 1950.12    5492 1951.18  5512.1 1950.85  5542.3 1951.48
    5549 1952.15  5562.4 1952.03  5602.6 1955.38  5642.8 1955.79  5647.9 1956.79
  5652.9 1956.53    5683  1958.8  5741.8 1961.09  5746.8 1960.65  5764.5 1961.95
#Mann= 3 ,-1 , 0
  4438.3     .05       0  4998.5     .05       0  5002.5     .05       0
Bank Sta=4998.5,5002.5
XS Rating Curve= 0 ,0
Exp/Cntr=0.3,0.1

Type RM Length L Ch R = 1 ,5249    ,92,92,92
BEGIN DESCRIPTION:
Mapping XS abd14cde
END DESCRIPTION:
XS GIS Cut Line= 6
      1567775.93      6775280.37      1568090.61       6774724.8
       1568207.8      6774700.93      1568288.09      6774661.86
      1568331.49      6774572.89      1568153.88      6773881.82
#Sta/Elev= 30
  4086.5 1951.09  4181.4  1951.2  4278.1 1949.26  4468.5 1948.94  4579.7 1946.62
  4652.4  1947.3  4687.9 1945.46  4729.5 1946.82  4779.8 1945.96  4784.9    1944
  4830.3 1945.65  4835.4 1944.13  4860.4 1945.55    4866 1943.42  4897.1 1942.76
  5150.4 1942.62  5150.7 1942.12  5154.4 1942.62  5180.3 1944.39  5200.5 1944.22
  5204.2 1945.85  5221.4 1944.46    5263 1946.27  5277.8 1947.92  5294.1 1946.94
  5356.6 1950.29  5449.8 1952.47  5503.8 1955.51  5709.3  1955.4  5746.9 1956.76
#Mann= 3 ,-1 , 0
  4086.5     .05       0  5150.4     .05       0  5154.4     .05       0
Bank Sta=5150.4,5154.4
XS Rating Curve= 0 ,0
Exp/Cntr=0.3,0.1

Type RM Length L Ch R = 1 ,5157    ,195,195,195
BEGIN DESCRIPTION:
Mapping XS 522bd040
END DESCRIPTION:
XS GIS Cut Line= 6
      1567791.13      6775315.08      1568134.01      6774744.33
      1568383.58       6774666.2      1568394.43      6774531.66
      1568290.26      6774243.03      1568193.04      6773841.18
#Sta/Elev= 30
  4067.2 1950.98  4586.3 1947.56  4696.3 1945.68  4775.3 1951.28  4795.5  1951.1
  4800.6 1948.94  4855.4 1951.06  4860.4  1949.8  4877.4  1950.9    4930 1947.24
  4978.7 1948.05  4997.7 1949.76  5018.5 1948.72  5108.9 1949.66  5170.4 1948.85
  5175.8 1947.73  5192.9 1949.02    5206 1947.88  5234.1    1949  5256.2 1947.55
  5297.4 1947.79  5333.4 1945.35  5333.6 1944.85  5337.4 1945.35  5389.2 1949.44
    5419 1949.12  5520.1 1951.35    5616  1954.5  5777.4 1954.82  5856.4 1957.28
#Mann= 3 ,-1 , 0
  4067.2     .05       0  5333.4     .05       0  5337.4     .05       0
Bank Sta=5333.4,5337.4
XS Rating Curve= 0 ,0
Exp/Cntr=0.3,0.1

Type RM Length L Ch R = 1 ,4962    ,481,481,481
BEGIN DESCRIPTION:
Mapping XS 3d705836
END DESCRIPTION:
XS GIS Cut Line= 3
      1568531.14       6775614.6      1568570.21       6775080.7
      1568529.03      6773951.58
#Sta/Elev= 30
  4026.7 1949.88  4203.8 1946.16    4287 1945.55  4344.1 1944.19  4568.7 1942.52
  4664.8 1940.66  4714.8 1941.12  4804.9 1940.64    4905 1941.95    4955  1940.3
    4975 1941.18    4995 1939.86    5035 1940.42    5043 1939.13  5043.3 1938.63
  5046.8 1938.63    5047 1939.13  5085.1 1942.15  5125.1 1942.86  5215.2 1942.42
  5385.3 1945.93  5405.3 1945.84  5445.3 1947.53  5565.4 1948.81  5575.4 1949.79
  5585.4 1949.71  5625.4 1951.72  5662.9 1955.83  5667.9  1955.3  5691.9 1956.68
#Mann= 3 ,-1 , 0
  4026.7     .05       0    5043     .05       0    5047     .05       0
Bank Sta=5043,5047
XS Rating Curve= 0 ,0
Exp/Cntr=0.3,0.1

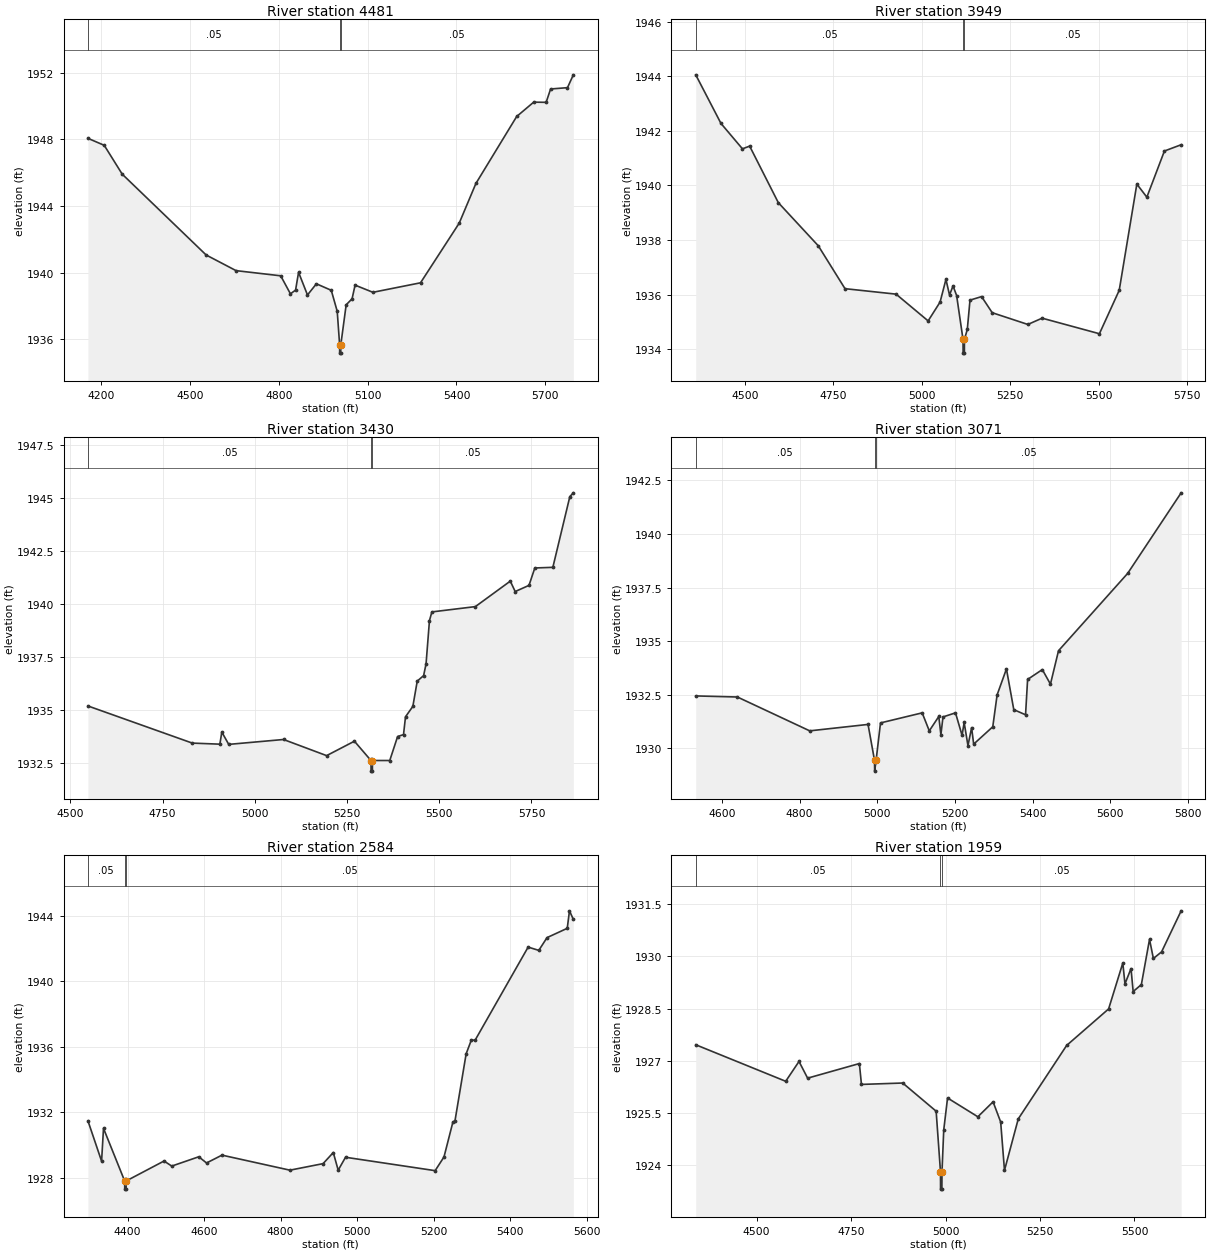
Type RM Length L Ch R = 1 ,4481    ,532,532,532
BEGIN DESCRIPTION:
Mapping XS a6c69a1c
END DESCRIPTION:
XS GIS Cut Line= 4
      1568874.02      6775612.41      1568947.81      6775128.44
      1568871.86      6774314.64      1568687.42      6774039.06
#Sta/Elev= 30
  4155.9 1948.06  4210.9 1947.64  4271.6 1945.91  4554.9 1941.06  4655.9 1940.12
  4806.6 1939.81  4839.4 1938.73  4856.8 1938.95  4866.9 1940.02    4897 1938.66
  4927.1 1939.33  4977.3 1938.94  4997.4 1937.68  5005.5 1935.67  5005.7 1935.17
  5009.2 1935.17  5009.5 1935.67  5027.6 1938.07  5047.5 1938.43  5057.7 1939.25
  5117.9 1938.82  5278.6 1939.39  5409.2 1942.97  5465.5 1945.35  5603.2 1949.37
  5660.6 1950.23  5702.6 1950.22  5717.7 1951.02  5774.7  1951.1  5794.4 1951.87
#Mann= 3 ,-1 , 0
  4155.9     .05       0  5005.5     .06       0  5009.5     .05       0
Bank Sta=5005.5,5009.5
XS Rating Curve= 0 ,0
Exp/Cntr=0.3,0.1

Type RM Length L Ch R = 1 ,3949    ,519,519,519
BEGIN DESCRIPTION:
Mapping XS 692602f9
END DESCRIPTION:
XS GIS Cut Line= 4
      1569394.87      6775408.36      1569449.12      6775069.85
      1569375.33      6774420.98      1569135.59      6774131.56
#Sta/Elev= 30
  4361.4 1944.05  4432.7 1942.27  4493.4 1941.34  4513.7 1941.44  4594.7 1939.37
  4707.7 1937.79  4783.2 1936.22  4927.5 1936.02  5018.1 1935.04  5051.9 1935.73
  5068.4 1936.56  5078.5 1935.99  5088.5 1936.32  5098.6 1935.97  5116.7 1934.36
    5117 1933.86  5120.5 1933.86  5120.7 1934.36  5128.8 1934.73  5136.4  1935.8
  5169.1 1935.93  5199.2 1935.34  5299.9 1934.91  5340.2 1935.14  5502.1 1934.57
  5558.1 1936.16  5607.9 1940.05  5636.2 1939.57  5685.8 1941.26  5733.1 1941.49
#Mann= 3 ,-1 , 0
  4361.4     .05       0  5116.7     .05       0  5120.7     .05       0
Bank Sta=5116.7,5120.7
XS Rating Curve= 0 ,0
Exp/Cntr=0.3,0.1

Type RM Length L Ch R = 1 ,3430    ,359,359,359
BEGIN DESCRIPTION:
Mapping XS f3d68ad1
END DESCRIPTION:
XS GIS Cut Line= 4
      1569844.08      6775032.92      1569865.78      6774748.67
      1569650.94      6774160.56      1569449.55      6773809.76
#Sta/Elev= 30
  4547.8 1935.19  4830.7 1933.44  4905.4 1933.39  4910.7 1933.96  4929.4 1933.38
    5078 1933.61  5194.8 1932.85  5270.1 1933.53    5315 1932.62  5315.3 1932.12
  5318.8 1932.12    5319 1932.62  5365.9 1932.62  5387.2 1933.75  5403.2 1933.84
  5408.6 1934.68  5428.5 1935.17  5440.4 1936.36  5457.7 1936.62  5464.3 1937.17
  5473.5 1939.21  5480.1 1939.62    5598 1939.87  5692.6 1941.07  5705.9 1940.58
  5743.3 1940.87  5759.1 1941.69    5808 1941.72    5854 1945.05  5863.5 1945.23
#Mann= 3 ,-1 , 0
  4547.8     .05       0    5315     .05       0    5319     .05       0
Bank Sta=5315,5319
XS Rating Curve= 0 ,0
Exp/Cntr=0.3,0.1

Type RM Length L Ch R = 1 ,3071    ,487,487,487
BEGIN DESCRIPTION:
Mapping XS 7dba85ef
END DESCRIPTION:
XS GIS Cut Line= 4
      1570178.28      6774839.83      1570156.58      6774559.87
      1569943.91      6774010.82       1569653.1      6773765.59
#Sta/Elev= 30
  4532.6 1932.44  4639.8 1932.39  4826.1 1930.81  4976.3 1931.11    4993 1929.43
  4993.3 1928.93    4997 1929.43  5008.4 1931.18  5115.7 1931.65    5134 1930.81
  5158.5 1931.48  5163.9 1930.63  5169.3 1931.46  5201.5 1931.65  5218.4  1930.6
  5223.8  1931.2  5233.6 1930.12    5243 1930.96  5248.3 1930.19  5297.5    1931
  5308.7 1932.49  5332.7  1933.7  5351.6  1931.8  5381.9 1931.56  5387.2 1933.21
  5425.1 1933.67    5446 1932.99  5466.8 1934.55  5644.9 1938.16  5782.6 1941.92
#Mann= 3 ,-1 , 0
  4532.6     .05       0    4993     .05       0    4997     .05       0
Bank Sta=4993,4997
XS Rating Curve= 0 ,0
Exp/Cntr=0.3,0.1

Type RM Length L Ch R = 1 ,2584    ,625,625,625
BEGIN DESCRIPTION:
Mapping XS d110c3a2
END DESCRIPTION:
XS GIS Cut Line= 4
      1570575.41      6774805.08      1570523.33        6774434.
      1570362.74      6773939.21      1570173.97       6773615.9
#Sta/Elev= 30
  4296.2 1931.47  4331.9    1929  4336.9 1931.01  4392.2 1927.79  4392.5 1927.29
    4396 1927.29  4396.2 1927.79  4495.2 1929.01  4515.4  1928.7  4586.1 1929.27
  4606.3 1928.89  4646.7 1929.37  4824.4 1928.45  4911.1 1928.85  4937.8 1929.53
  4950.6 1928.45  4969.8 1929.24  5204.1 1928.42  5227.3 1929.26  5250.3 1931.37
  5256.1 1931.48  5285.2 1935.57  5299.1 1936.43  5308.3 1936.39  5447.3  1942.1
  5475.2  1941.9  5496.7 1942.68  5549.6 1943.25  5555.4 1944.32  5565.5  1943.8
#Mann= 3 ,-1 , 0
  4296.2     .05       0  4392.2     .05       0  4396.2     .05       0
Bank Sta=4392.2,4396.2
XS Rating Curve= 0 ,0
Exp/Cntr=0.3,0.1

Type RM Length L Ch R = 1 ,1959    ,345,345,345
BEGIN DESCRIPTION:
Mapping XS 28c2fd4b
END DESCRIPTION:
XS GIS Cut Line= 4
      1570755.53      6774683.58      1570981.23      6774201.79
      1570944.34      6773822.02      1570620.98      6773639.72
#Sta/Elev= 30
  4338.8 1927.46  4576.9 1926.41  4612.1 1926.98  4634.9  1926.5  4771.9 1926.92
  4777.4 1926.32  4886.6 1926.36  4975.1 1925.55  4986.6 1923.81  4986.8 1923.31
  4990.3 1923.31  4990.6 1923.81  4995.2 1925.01  5005.3 1925.93  5085.5 1925.39
  5125.8 1925.82  5145.9 1925.24    5156 1923.85  5192.5 1925.33  5320.5 1927.44
  5431.6 1928.49  5469.2 1929.81  5474.9 1929.21  5490.9 1929.65  5496.6 1928.99
  5518.3 1929.19  5539.9 1930.49  5550.1 1929.94  5571.8 1930.13  5623.6 1931.31
#Mann= 3 ,-1 , 0
  4338.8     .05       0  4986.6     .05       0  4990.6     .05       0
Bank Sta=4986.6,4990.6
XS Rating Curve= 0 ,0
Exp/Cntr=0.3,0.1

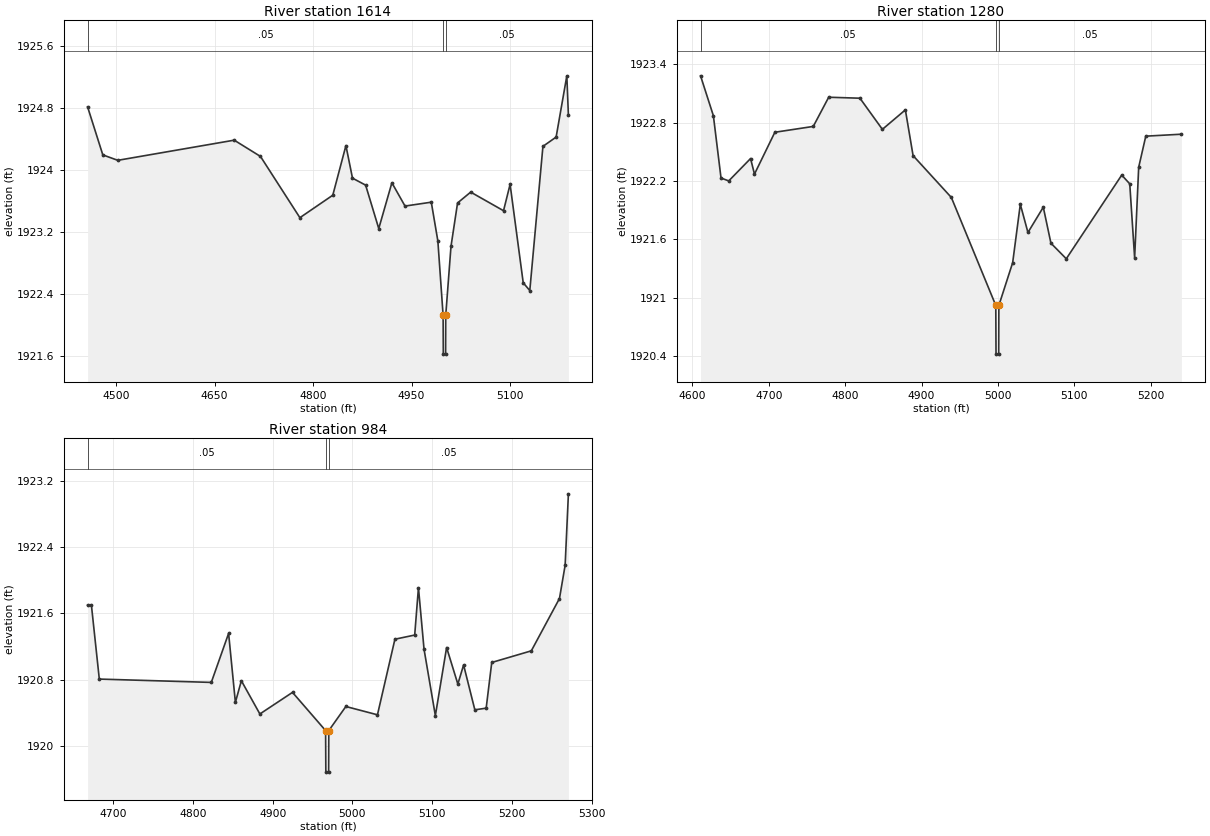
Type RM Length L Ch R = 1 ,1614    ,334,334,334
BEGIN DESCRIPTION:
Mapping XS 6b25e47c
END DESCRIPTION:
XS GIS Cut Line= 3
      1571218.65      6774531.19      1571229.06      6774193.98
      1571219.97      6773799.26
#Sta/Elev= 30
  4456.6 1924.81  4479.8 1924.19  4502.6 1924.12  4679.9 1924.38  4719.9 1924.17
  4779.9 1923.38    4830 1923.67    4850 1924.31    4860 1923.89    4880  1923.8
    4900 1923.24    4920 1923.83    4940 1923.53    4980 1923.58    4990 1923.08
    4998 1922.12  4998.3 1921.62  5001.8 1921.62    5002 1922.12    5010 1923.01
    5020 1923.57    5040 1923.71    5090 1923.47    5100 1923.81    5120 1922.54
    5130 1922.44    5150  1924.3  5170.1 1924.42  5186.4 1925.21  5188.8  1924.7
#Mann= 3 ,-1 , 0
  4456.6     .05       0    4998     .03       0    5002     .05       0
Bank Sta=4998,5002
XS Rating Curve= 0 ,0
Exp/Cntr=0.3,0.1

Type RM Length L Ch R = 1 ,1280    ,296,296,296
BEGIN DESCRIPTION:
Mapping XS 7e5d8acc
END DESCRIPTION:
XS GIS Cut Line= 4
      1571492.09      6774524.67      1571515.52      6774321.59
      1571492.08      6774029.92      1571451.73      6773903.65
#Sta/Elev= 30
  4610.6 1923.28  4627.4 1922.87  4637.4 1922.23  4647.5  1922.2  4676.1 1922.43
  4681.2 1922.27  4707.9  1922.7  4758.2 1922.76  4778.4 1923.06  4819.3 1923.05
  4848.7 1922.73  4878.8 1922.93  4888.9 1922.46    4939 1922.03  4997.2 1920.92
  4997.5 1920.42    5001 1920.42  5001.2 1920.92  5019.3 1921.36  5029.3 1921.96
  5039.3 1921.67  5059.4 1921.93  5069.4 1921.56  5089.5  1921.4  5162.1 1922.26
  5172.6 1922.17    5179 1921.41  5184.3 1922.34  5193.6 1922.66  5240.2 1922.68
#Mann= 3 ,-1 , 0
  4610.6     .05       0  4997.2     .03       0  5001.2     .05       0
Bank Sta=4997.2,5001.2
XS Rating Curve= 0 ,0
Exp/Cntr=0.3,0.1

Type RM Length L Ch R = 1 ,984     ,0,0,0
BEGIN DESCRIPTION:
Elm 01 70 3776.858
END DESCRIPTION:
XS GIS Cut Line= 5
      1571763.26      6774432.64      1571776.16      6774256.26
      1571800.86      6774140.47      1571756.62      6774039.25
      1571618.89      6773898.29
#Sta/Elev= 30
    4668  1921.7  4672.8  1921.7  4682.7 1920.81  4823.1 1920.77  4844.8 1921.36
  4853.3 1920.53  4860.8 1920.79    4884 1920.39  4924.9 1920.65  4966.4 1920.19
  4966.7 1919.69  4970.2 1919.69  4970.4 1920.19  4991.8 1920.48  5031.4 1920.38
  5053.3 1921.29  5078.1 1921.34  5082.8 1921.91  5089.8 1921.17    5104 1920.37
  5118.1 1921.19  5132.2 1920.75  5139.4 1920.98  5153.5 1920.44  5167.7 1920.46
  5174.7 1921.01  5224.3 1921.15  5259.6 1921.78  5266.7 1922.18  5270.8 1923.04
#Mann= 3 ,-1 , 0
    4668     .05       0  4966.4     .03       0  4970.4     .05       0
Bank Sta=4966.4,4970.4
XS Rating Curve= 0 ,0
Exp/Cntr=0.3,0.1

Chan Stop Cuts=-1
Use User Specified Reach Order=0
Composite Channel Slope=5