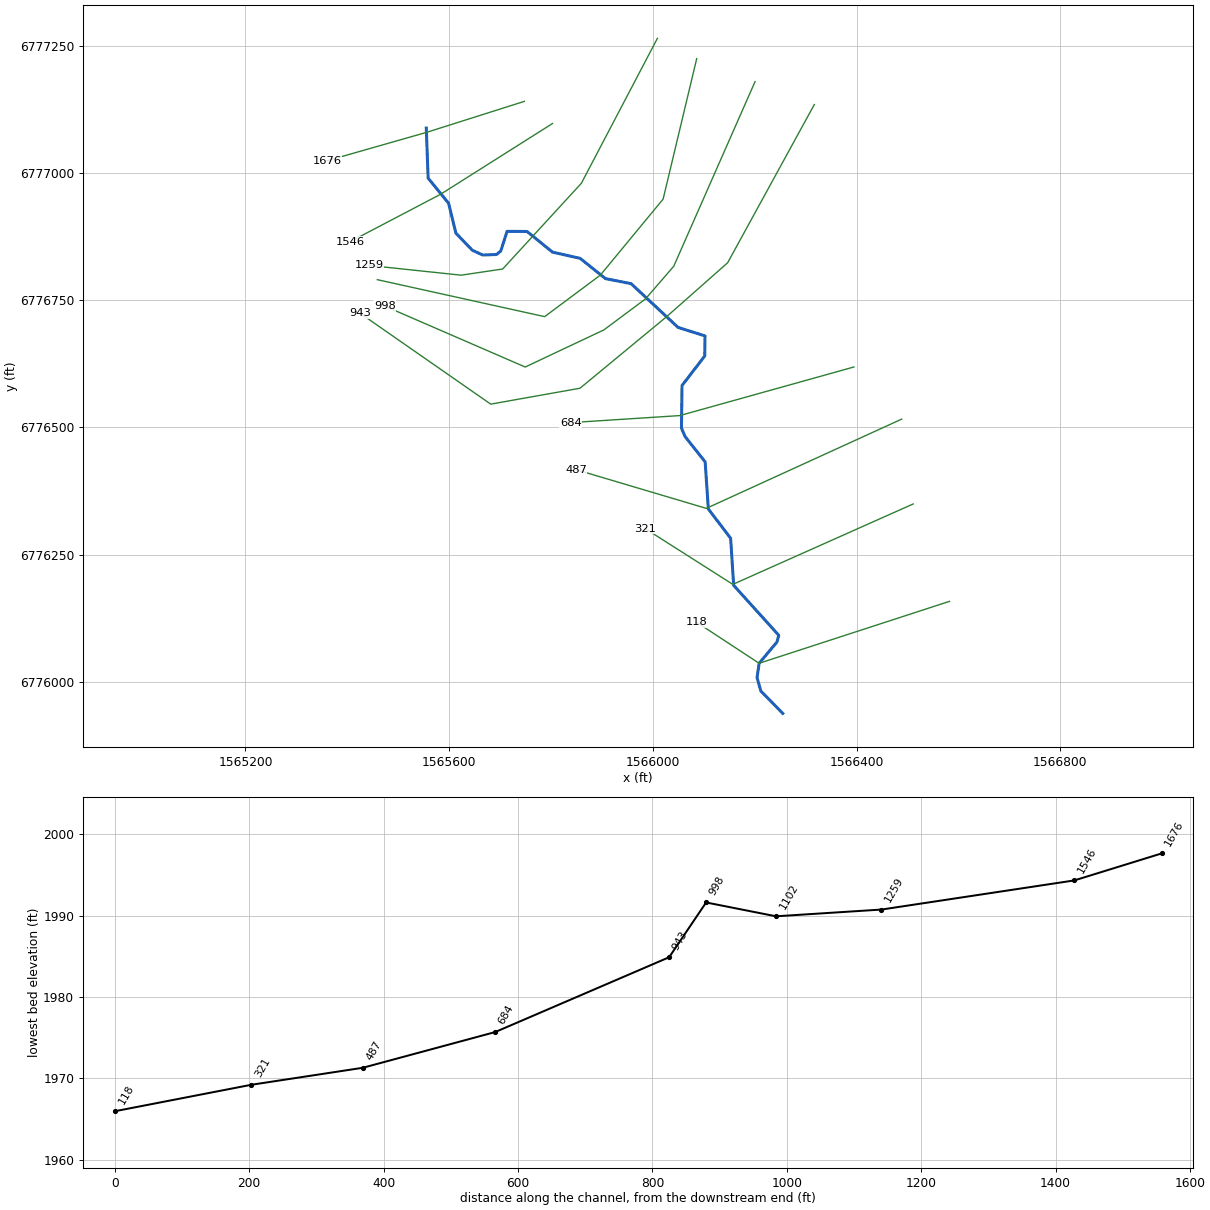
--- Elm 01 71.prj (project) ---

Proj Title=Elm 01 71 Base Level Engineering
Current Plan=p01
Default Exp/Contr=0.3,0.1
English Units
Geom File=g01
Flow File=f01
Plan File=p01
BEGIN DESCRIPTION:
Elm 01 71
END DESCRIPTION:

--- Elm 01 71.p01 (plan) ---

Plan Title=Multiple Run
Short Identifier=Multiple
Geom File=g01
Flow File=f01
Subcritical Flow
K Sum by GR= 0
Std Step Tol= 0.01
Critical Tol= 0.01
Num of Std Step Trials= 20
Max Error Tol= 0.3
Flow Tol Ratio= 0.001
Split Flow NTrial= 30
Split Flow Tol= 0.02
Split Flow Ratio= 0.02
Log Output Level= 0
Friction Slope Method= 1
Unsteady Friction Slope Method= 2
Unsteady Bridges Friction Slope Method= 1
Parabolic Critical Depth
Global Vel Dist=  1 , 1 , 1
Global Log Level= 0
CheckData=True
Encroach Param= -1, 0, 0, 0
BEGIN DESCRIPTION:
Multiple Run
END DESCRIPTION:

--- Elm 01 71.f01 (steady flow) ---

Flow Title=Multiple
Number of Profiles=7
Profile Names=10-year,25-year,50-year,1pct_min,100-year,1pct_plu,500-year
River Rch & RM= Elm 01 71,Reach-1,1676
      40      49      56      40      64      87      84
Boundary for River Rch & Prof#=Elm 01 71,Reach-1,1
Up Type=0
Dn Type=3
Dn Slope=0.001
Boundary for River Rch & Prof#=Elm 01 71,Reach-1,2
Up Type=0
Dn Type=3
Dn Slope=0.001
Boundary for River Rch & Prof#=Elm 01 71,Reach-1,3
Up Type=0
Dn Type=3
Dn Slope=0.001
Boundary for River Rch & Prof#=Elm 01 71,Reach-1,4
Up Type=0
Dn Type=3
Dn Slope=0.001
Boundary for River Rch & Prof#=Elm 01 71,Reach-1,5
Up Type=0
Dn Type=3
Dn Slope=0.001
Boundary for River Rch & Prof#=Elm 01 71,Reach-1,6
Up Type=0
Dn Type=3
Dn Slope=0.001
Boundary for River Rch & Prof#=Elm 01 71,Reach-1,7
Up Type=0
Dn Type=3
Dn Slope=0.001

--- Elm 01 71.g01 (geometry) ---

Geom Title=Existing Conditions

River Reach=Elm 01 71,Reach-1
Reach XY= 30
      1565555.00      6777088.00      1565558.63      6776989.50
      1565598.88      6776940.15      1565613.06      6776881.55
      1565645.25      6776847.98      1565665.83      6776838.46
      1565692.80      6776839.50      1565701.27      6776846.28
      1565713.62      6776884.91      1565752.93      6776884.75
      1565802.77      6776844.17      1565857.19      6776831.93
      1565906.74      6776792.19      1565957.29      6776782.15
      1566049.36      6776696.30      1566102.37      6776679.52
      1566101.81      6776640.11      1566057.20      6776582.06
      1566056.10      6776498.55      1566063.09      6776481.96
      1566102.64      6776432.03      1566108.85      6776339.60
      1566152.64      6776282.02      1566158.64      6776189.50
      1566247.19      6776091.40      1566243.65      6776078.13
      1566208.61      6776036.42      1566204.54      6776008.25
      1566211.98      6775981.86      1566255.00      6775938.00

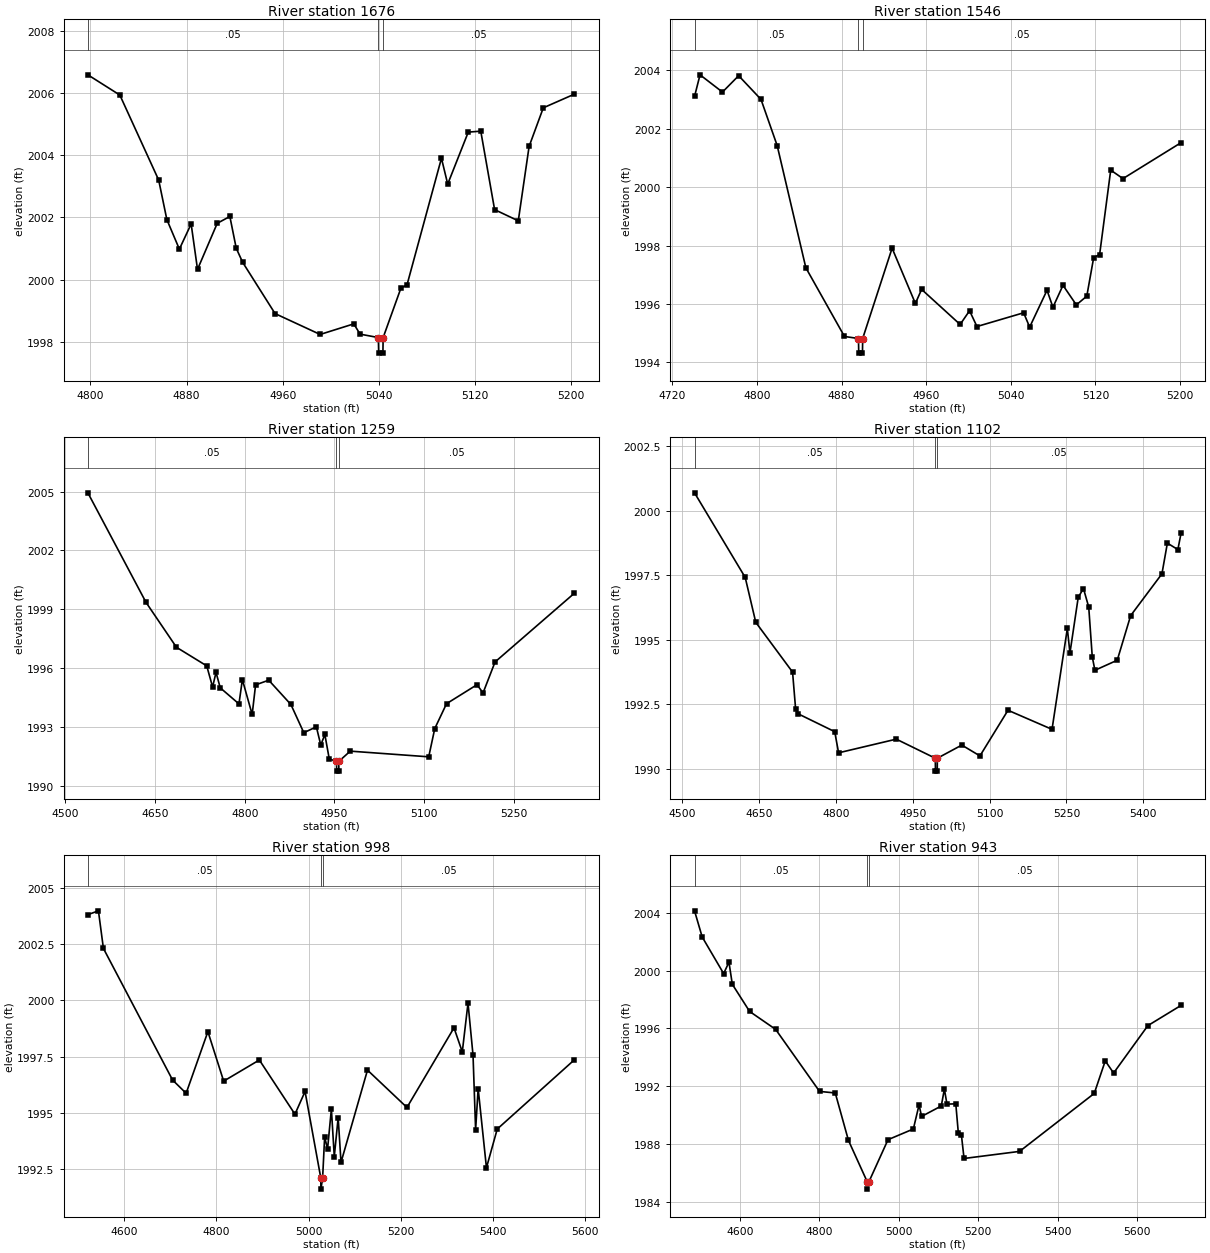
Type RM Length L Ch R = 1,1676,130,130,130
BEGIN DESCRIPTION:
Elm 01 71 1475.361
END DESCRIPTION:
XS GIS Cut Line= 3
      1565747.59      6777140.34      1565554.94      6777079.24
      1565360.11      6777023.68
#Sta/Elev= 30
  4797.9 2006.58  4824.5 2005.93  4856.8 2003.20  4863.6 2001.93  4874.0 2000.98
  4883.8 2001.79  4889.1 2000.33  4905.5 2001.81  4916.0 2002.03  4921.3 2001.01
  4926.6 2000.56  4953.6 1998.91  4991.1 1998.24  5019.1 1998.58  5024.3 1998.25
  5039.5 1998.14  5039.8 1997.64  5043.3 1997.64  5043.5 1998.14  5058.2 1999.72
  5063.4 1999.84  5092.0 2003.90  5097.2 2003.07  5114.3 2004.74  5124.7 2004.77
  5136.2 2002.25  5155.9 2001.89  5164.9 2004.28  5176.7 2005.52  5202.6 2005.96
#Mann=3,-1,0
  4797.9    0.05       0  5039.5    0.05       0  5043.5    0.05       0
Bank Sta=5039.5,5043.5
Exp/Cntr=0.3,0.1

Type RM Length L Ch R = 1,1546,287,287,287
BEGIN DESCRIPTION:
Elm 01 71 1546.05
END DESCRIPTION:
XS GIS Cut Line= 3
      1565802.82      6777096.78      1565583.17      6776957.87
      1565406.13      6776865.01
#Sta/Elev= 30
  4741.1 2003.10  4746.3 2003.84  4767.5 2003.25  4782.8 2003.81  4803.9 2003.00
  4819.2 2001.42  4846.3 1997.24  4882.8 1994.89  4896.0 1994.82  4896.3 1994.32
  4899.8 1994.32  4900.0 1994.82  4927.8 1997.91  4949.8 1996.02  4955.7 1996.50
  4992.1 1995.30  5001.0 1995.77  5008.0 1995.23  5052.1 1995.70  5057.8 1995.21
  5074.2 1996.47  5079.8 1995.89  5089.3 1996.64  5101.9 1995.97  5111.8 1996.27
  5118.3 1997.59  5123.9 1997.69  5134.4 2000.58  5146.0 2000.29  5200.9 2001.52
#Mann=3,-1,0
  4741.1    0.05       0  4896.0    0.05       0  4900.0    0.05       0
Bank Sta=4896,4900
Exp/Cntr=0.3,0.1

Type RM Length L Ch R = 1,1259,157,157,157
BEGIN DESCRIPTION:
Mapping XS 08b1b69f
END DESCRIPTION:
XS GIS Cut Line= 5
      1566008.87      6777264.16      1565859.56      6776979.43
      1565705.05      6776811.02      1565623.45      6776798.87
      1565442.91      6776817.97
#Sta/Elev= 30
  4537.5 2004.94  4634.8 1999.35  4685.7 1997.06  4736.4 1996.11  4746.2 1995.03
  4751.9 1995.78  4759.0 1994.99  4790.3 1994.17  4796.0 1995.41  4812.4 1993.63
  4818.1 1995.14  4840.1 1995.38  4877.2 1994.14  4898.8 1992.70  4919.8 1993.00
  4927.2 1992.07  4934.0 1992.61  4941.4 1991.36  4953.5 1991.24  4953.8 1990.74
  4957.3 1990.74  4957.5 1991.24  4976.5 1991.76  5107.8 1991.47  5117.9 1992.91
  5137.6 1994.18  5188.6 1995.15  5198.7 1994.73  5218.8 1996.31  5351.6 1999.82
#Mann=3,-1,0
  4537.5    0.05       0  4953.5    0.05       0  4957.5    0.05       0
Bank Sta=4953.5,4957.5
Exp/Cntr=0.3,0.1

Type RM Length L Ch R = 1,1102,104,104,104
BEGIN DESCRIPTION:
Elm 01 71 1102.07
END DESCRIPTION:
XS GIS Cut Line= 5
      1566086.06      6777224.30      1566020.09      6776948.30
      1565896.83      6776799.00      1565787.46      6776717.40
      1565458.84      6776790.04
#Sta/Elev= 30
  4523.5 2000.70  4622.5 1997.42  4643.1 1995.68  4715.0 1993.75  4720.9 1992.33
  4726.1 1992.13  4797.3 1991.44  4804.9 1990.62  4917.6 1991.15  4993.8 1990.41
  4994.1 1989.91  4997.6 1989.91  4997.8 1990.41  5045.6 1990.92  5081.0 1990.50
  5135.8 1992.27  5221.8 1991.53  5251.7 1995.44  5256.8 1994.49  5273.0 1996.65
  5283.2 1996.99  5293.5 1996.27  5300.4 1994.34  5305.6 1993.82  5349.2 1994.21
  5375.4 1995.94  5436.5 1997.56  5447.1 1998.75  5467.6 1998.50  5473.9 1999.14
#Mann=3,-1,0
  4523.5    0.05       0  4993.8    0.05       0  4997.8    0.05       0
Bank Sta=4993.8,4997.8
Exp/Cntr=0.3,0.1

Type RM Length L Ch R = 1,998,55,55,55
BEGIN DESCRIPTION:
Elm 01 71 997.64
END DESCRIPTION:
XS GIS Cut Line= 6
      1566200.65      6777179.19      1566040.93      6776816.36
      1565985.37      6776752.12      1565903.78      6776691.36
      1565749.26      6776618.44      1565473.24      6776738.22
#Sta/Elev= 30
  4521.1 2003.81  4544.0 2003.98  4554.8 2002.31  4704.8 1996.46  4734.2 1995.87
  4781.4 1998.61  4815.6 1996.41  4893.0 1997.35  4970.2 1994.94  4992.1 1995.95
  5026.2 1992.11  5026.5 1991.61  5030.2 1992.11  5034.6 1993.93  5040.9 1993.39
  5049.2 1995.17  5055.5 1993.06  5063.9 1994.79  5070.1 1992.80  5127.5 1996.90
  5213.1 1995.24  5315.1 1998.78  5333.1 1997.71  5345.5 1999.88  5356.4 1997.56
  5362.0 1994.25  5367.5 1996.08  5385.5 1992.56  5408.9 1994.28  5576.3 1997.36
#Mann=3,-1,0
  4521.1    0.05       0  5026.2    0.03       0  5030.2    0.05       0
Bank Sta=5026.2,5030.2
Exp/Cntr=0.3,0.1

Type RM Length L Ch R = 1,943,259,259,259
BEGIN DESCRIPTION:
Elm 01 71 943.41
END DESCRIPTION:
XS GIS Cut Line= 6
      1566316.97      6777134.07      1566146.83      6776823.30
      1566027.04      6776717.40      1565856.90      6776576.77
      1565681.55      6776545.52      1565425.58      6776723.67
#Sta/Elev= 30
  4485.6 2004.13  4504.9 2002.32  4558.9 1999.79  4572.3 2000.58  4580.7 1999.05
  4624.3 1997.17  4689.8 1995.93  4800.3 1991.64  4839.9 1991.53  4873.1 1988.25
  4920.5 1985.38  4920.7 1984.88  4924.5 1985.38  4972.7 1988.30  5036.5 1989.04
  5050.8 1990.70  5057.3 1989.91  5106.8 1990.63  5114.6 1991.80  5121.1 1990.76
  5143.3 1990.78  5149.8 1988.74  5157.6 1988.59  5164.1 1987.00  5303.9 1987.49
  5491.9 1991.50  5519.6 1993.75  5540.6 1992.91  5626.9 1996.19  5710.5 1997.59
#Mann=3,-1,0
  4485.6    0.05       0  4920.5    0.05       0  4924.5    0.05       0
Bank Sta=4920.5,4924.5
Exp/Cntr=0.3,0.1

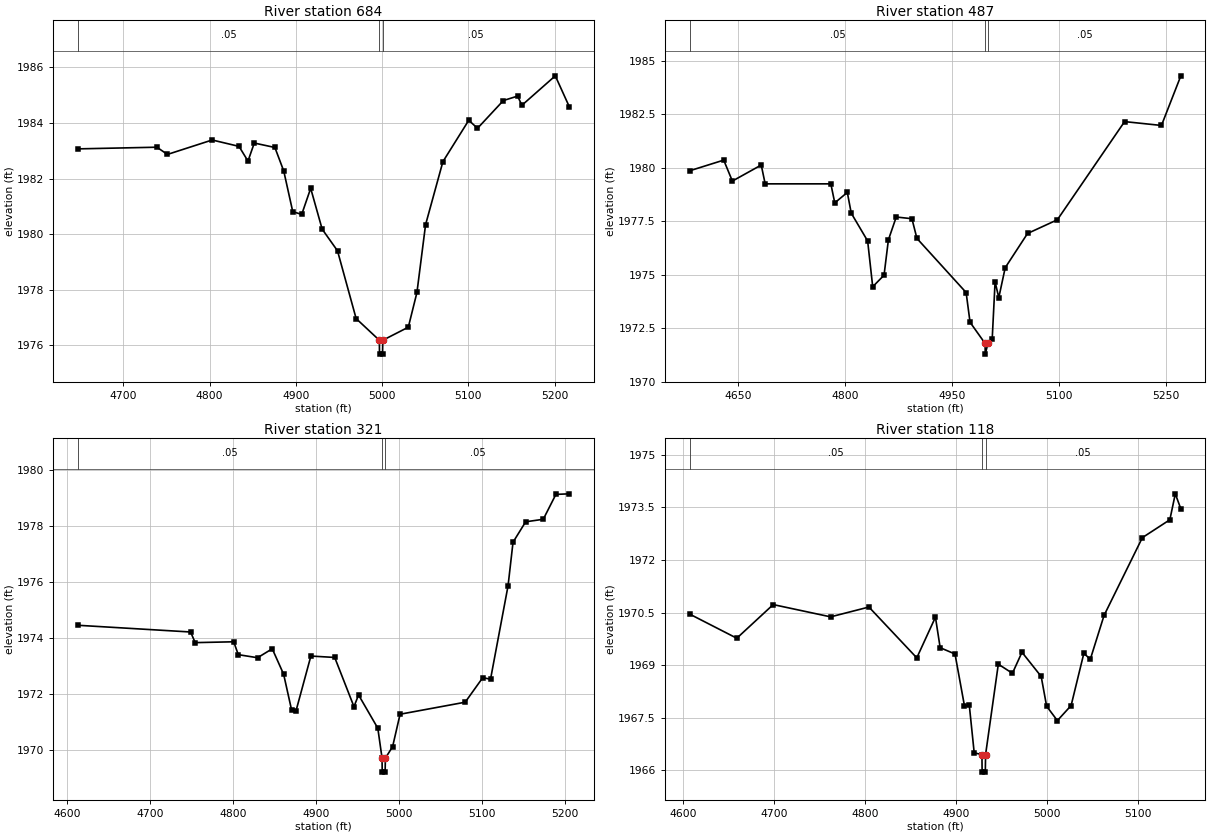
Type RM Length L Ch R = 1,684,197,197,197
BEGIN DESCRIPTION:
Elm 01 71 684.02
END DESCRIPTION:
XS GIS Cut Line= 3
      1566394.86      6776618.53      1566052.82      6776523.04
      1565838.79      6776509.23
#Sta/Elev= 30
  4647.3 1983.07  4738.8 1983.13  4751.0 1982.87  4802.9 1983.39  4834.0 1983.16
  4844.4 1982.63  4851.7 1983.28  4875.6 1983.12  4885.9 1982.27  4896.3 1980.81
  4906.7 1980.71  4917.1 1981.65  4930.4 1980.18  4948.2 1979.40  4969.8 1976.96
  4996.7 1976.18  4996.9 1975.68  5000.4 1975.68  5000.7 1976.18  5030.3 1976.65
  5040.3 1977.90  5050.3 1980.34  5070.4 1982.61  5100.4 1984.10  5110.5 1983.81
  5140.5 1984.81  5157.0 1984.97  5162.0 1984.64  5200.7 1985.70  5216.9 1984.59
#Mann=3,-1,0
  4647.3    0.05       0  4996.7    0.05       0  5000.7    0.05       0
Bank Sta=4996.7,5000.7
Exp/Cntr=0.3,0.1

Type RM Length L Ch R = 1,487,166,166,166
BEGIN DESCRIPTION:
Elm 01 71 486.75
END DESCRIPTION:
XS GIS Cut Line= 3
      1566488.59      6776516.10      1566104.90      6776340.75
      1565848.94      6776416.85
#Sta/Elev= 30
  4581.9 1979.86  4629.8 1980.36  4641.9 1979.38  4682.4 1980.13  4687.9 1979.25
  4780.0 1979.25  4785.5 1978.36  4803.1 1978.85  4808.6 1977.88  4831.6 1976.58
  4838.7 1974.44  4854.6 1974.98  4860.7 1976.63  4871.7 1977.70  4893.7 1977.62
  4900.7 1976.70  4969.7 1974.17  4975.2 1972.78  4996.3 1971.79  4996.5 1971.29
  5000.3 1971.79  5006.3 1972.02  5010.3 1974.67  5015.5 1973.93  5024.5 1975.33
  5055.8 1976.93  5097.6 1977.57  5191.9 1982.16  5243.6 1981.98  5270.8 1984.30
#Mann=3,-1,0
  4581.9    0.05       0  4996.3    0.05       0  5000.3    0.05       0
Bank Sta=4996.3,5000.3
Exp/Cntr=0.3,0.1

Type RM Length L Ch R = 1,321,203,203,203
BEGIN DESCRIPTION:
Elm 01 71 321
END DESCRIPTION:
XS GIS Cut Line= 3
      1566511.14      6776349.42      1566156.99      6776191.44
      1565985.13      6776300.81
#Sta/Elev= 30
  4613.5 1974.45  4749.1 1974.21  4754.6 1973.83  4801.0 1973.86  4806.5 1973.40
  4829.7 1973.29  4847.4 1973.61  4861.1 1972.70  4870.7 1971.42  4876.1 1971.40
  4893.9 1973.35  4922.6 1973.30  4945.8 1971.54  4951.3 1971.96  4974.5 1970.77
  4979.6 1969.70  4979.8 1969.20  4983.3 1969.20  4983.6 1969.70  4992.3 1970.11
  5001.3 1971.27  5079.7 1971.70  5100.9 1972.58  5110.2 1972.52  5131.3 1975.86
  5137.3 1977.42  5152.5 1978.15  5173.7 1978.24  5188.9 1979.13  5205.0 1979.15
#Mann=3,-1,0
  4613.5    0.05       0  4979.6    0.05       0  4983.6    0.05       0
Bank Sta=4979.6,4983.6
Exp/Cntr=0.3,0.1

Type RM Length L Ch R = 1,118,0,0,0
BEGIN DESCRIPTION:
Elm 01 71 975.61
END DESCRIPTION:
XS GIS Cut Line= 3
      1566582.42      6776158.06      1566208.61      6776036.42
      1566085.90      6776116.99
#Sta/Elev= 30
  4606.9 1970.46  4658.8 1969.77  4698.8 1970.73  4761.9 1970.38  4804.0 1970.66
  4856.6 1969.21  4877.1 1970.37  4882.3 1969.50  4898.6 1969.32  4909.0 1967.84
  4914.3 1967.86  4919.7 1966.50  4928.2 1966.45  4928.4 1965.95  4931.9 1965.95
  4932.2 1966.45  4946.2 1969.03  4961.7 1968.77  4972.2 1969.37  4993.3 1968.68
  4999.3 1967.83  5011.1 1967.42  5026.2 1967.85  5040.2 1969.34  5047.3 1969.17
  5062.4 1970.42  5104.5 1972.64  5134.7 1973.15  5140.7 1973.89  5146.8 1973.46
#Mann=3,-1,0
  4606.9    0.05       0  4928.2    0.05       0  4932.2    0.05       0
Bank Sta=4928.2,4932.2
Exp/Cntr=0.3,0.1

Chan Stop Cuts=-1