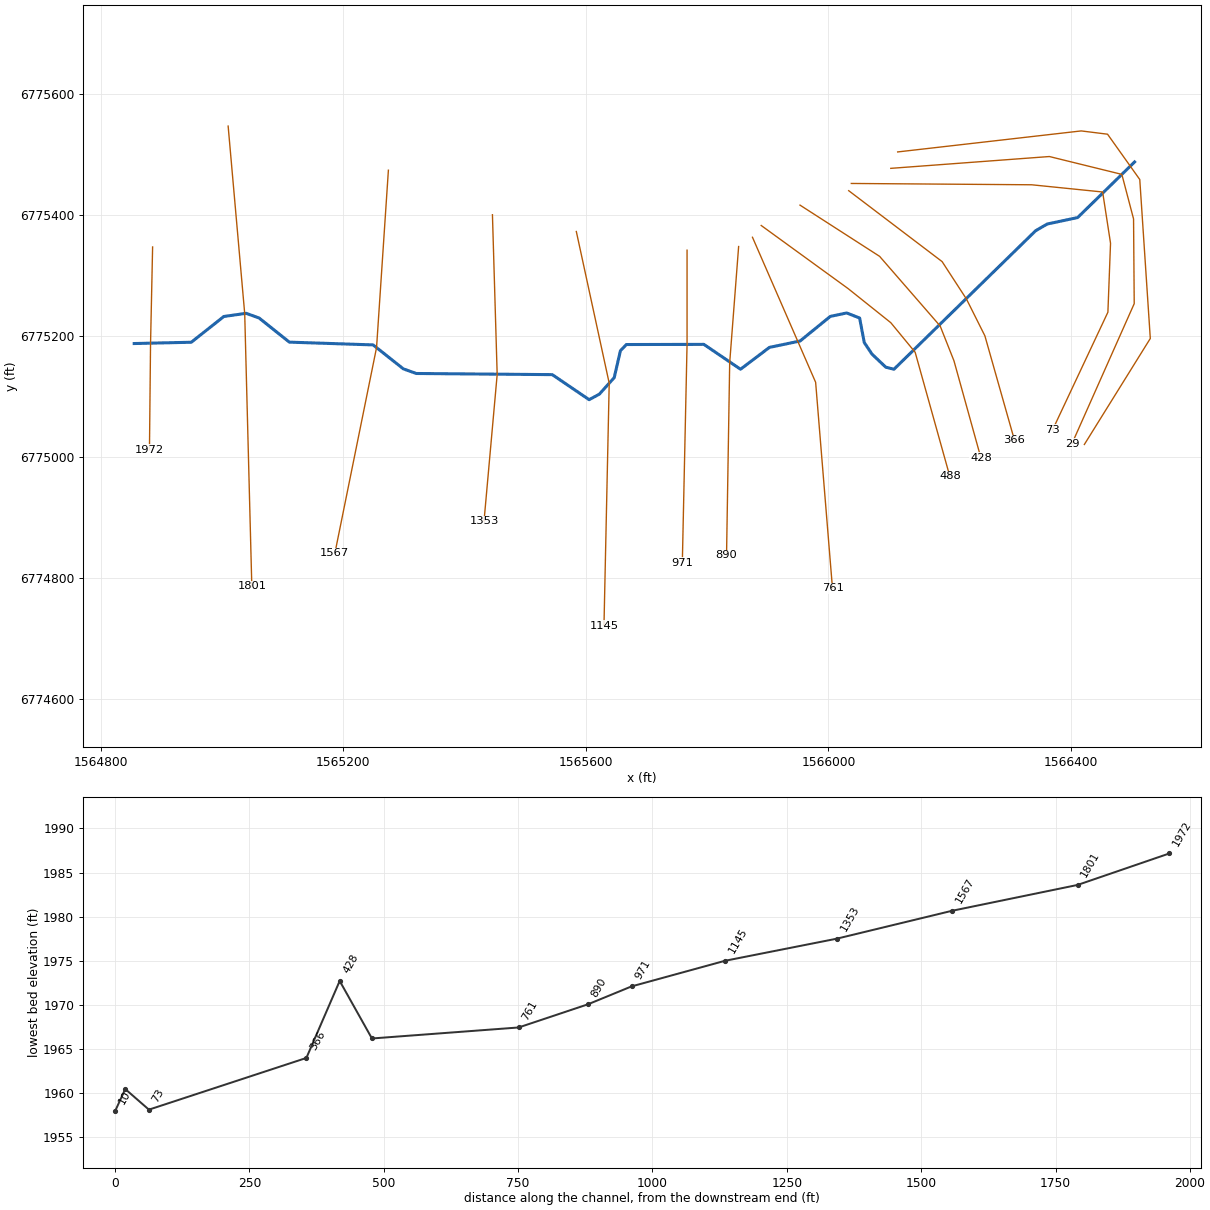
--- Elm 01 72.prj (project) ---

Proj Title=Elm 01 72 Base Level Engineering
Current Plan=p01
Default Exp/Contr=0.3,0.1
English Units
Geom File=g01
Flow File=f01
Plan File=p01
BEGIN DESCRIPTION:
Elm 01 72
END DESCRIPTION:

--- Elm 01 72.p01 (plan) ---

Plan Title=Multiple Run
Short Identifier=Multiple
Geom File=g01
Flow File=f01
Subcritical Flow
K Sum by GR= 0
Std Step Tol= 0.01
Critical Tol= 0.01
Num of Std Step Trials= 20
Max Error Tol= 0.3
Flow Tol Ratio= 0.001
Split Flow NTrial= 30
Split Flow Tol= 0.02
Split Flow Ratio= 0.02
Log Output Level= 0
Friction Slope Method= 1
Unsteady Friction Slope Method= 2
Unsteady Bridges Friction Slope Method= 1
Parabolic Critical Depth
Global Vel Dist=  1 , 1 , 1
Global Log Level= 0
CheckData=True
Encroach Param= -1, 0, 0, 0
BEGIN DESCRIPTION:
Multiple Run
END DESCRIPTION:

--- Elm 01 72.f01 (steady flow) ---

Flow Title=Multiple
Number of Profiles=7
Profile Names=10-year,25-year,50-year,1pct_min,100-year,1pct_plu,500-year
River Rch & RM= Elm 01 72,Reach-1,1972
      33      40      45      32      51      71      66
River Rch & RM= Elm 01 72,Reach-1,73
     172     233     282     213     341     469     503
Boundary for River Rch & Prof#=Elm 01 72,Reach-1,1
Up Type=0
Dn Type=3
Dn Slope=0.001
Boundary for River Rch & Prof#=Elm 01 72,Reach-1,2
Up Type=0
Dn Type=3
Dn Slope=0.001
Boundary for River Rch & Prof#=Elm 01 72,Reach-1,3
Up Type=0
Dn Type=3
Dn Slope=0.001
Boundary for River Rch & Prof#=Elm 01 72,Reach-1,4
Up Type=0
Dn Type=3
Dn Slope=0.001
Boundary for River Rch & Prof#=Elm 01 72,Reach-1,5
Up Type=0
Dn Type=3
Dn Slope=0.001
Boundary for River Rch & Prof#=Elm 01 72,Reach-1,6
Up Type=0
Dn Type=3
Dn Slope=0.001
Boundary for River Rch & Prof#=Elm 01 72,Reach-1,7
Up Type=0
Dn Type=3
Dn Slope=0.001

--- Elm 01 72.g01 (geometry) ---

Geom Title=Existing Conditions

River Reach=Elm 01 72,Reach-1
Reach XY= 30
      1564855.00      6775188.00      1564949.14      6775190.13
      1565002.81      6775232.67      1565039.61      6775237.91
      1565060.92      6775230.19      1565110.93      6775190.30
      1565249.06      6775185.73      1565298.94      6775146.14
      1565320.22      6775138.52      1565544.57      6775136.61
      1565605.30      6775095.26      1565622.05      6775104.23
      1565646.70      6775131.66      1565656.98      6775176.22
      1565666.83      6775186.35      1565794.55      6775186.63
      1565855.01      6775145.53      1565902.71      6775181.61
      1565953.29      6775192.20      1566003.15      6775232.82
      1566030.12      6775238.52      1566051.46      6775230.18
      1566059.13      6775189.67      1566071.73      6775170.65
      1566094.70      6775148.88      1566108.16      6775145.54
      1566341.79      6775374.37      1566361.04      6775385.48
      1566411.07      6775396.11      1566505.00      6775488.00

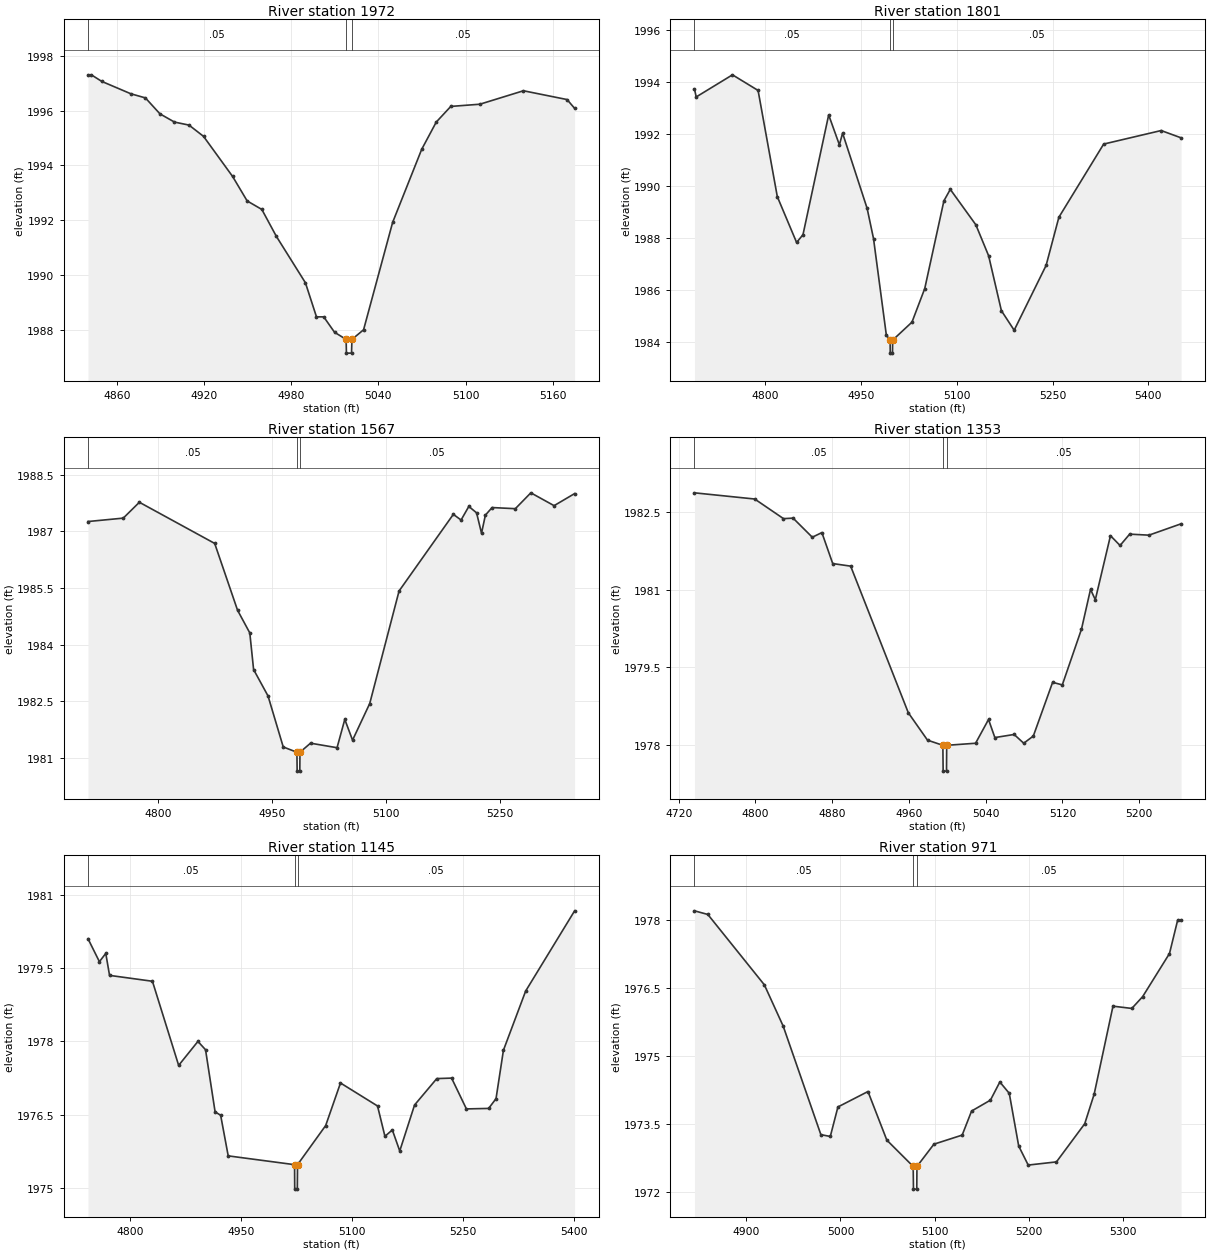
Type RM Length L Ch R = 1,1972,171,171,171
BEGIN DESCRIPTION:
Elm 01 72 1043.679
END DESCRIPTION:
XS GIS Cut Line= 3
      1564885.34      6775347.52      1564881.92      6775187.76
      1564880.14      6775012.77
#Sta/Elev= 30
  4840.2 1997.30  4842.5 1997.30  4849.7 1997.06  4869.7 1996.61  4879.7 1996.46
  4889.7 1995.88  4899.7 1995.58  4909.7 1995.47  4919.7 1995.06  4939.7 1993.60
  4949.7 1992.71  4959.8 1992.40  4969.8 1991.42  4989.8 1989.73  4997.4 1988.49
  5002.4 1988.49  5009.8 1987.93  5017.8 1987.67  5018.0 1987.17  5021.5 1987.17
  5021.8 1987.67  5029.8 1988.02  5049.8 1991.93  5069.8 1994.59  5079.8 1995.58
  5089.8 1996.15  5109.8 1996.23  5139.8 1996.72  5169.8 1996.40  5175.0 1996.08
#Mann=3,-1,0
  4840.2    0.05       0  5017.8    0.05       0  5021.8    0.05       0
Bank Sta=5017.8,5021.8
Exp/Cntr=0.3,0.1

Type RM Length L Ch R = 1,1801,234,234,234
BEGIN DESCRIPTION:
Elm 01 72 1801.01
END DESCRIPTION:
XS GIS Cut Line= 3
      1565009.91      6775547.25      1565037.25      6775237.31
      1565048.97      6774786.80
#Sta/Elev= 30
  4689.4 1993.74  4692.1 1993.43  4748.9 1994.28  4789.0 1993.68  4819.1 1989.60
  4849.3 1987.84  4859.3 1988.14  4899.5 1992.74  4916.3 1991.59  4921.3 1992.04
  4959.7 1989.15  4969.7 1987.99  4989.8 1984.28  4995.7 1984.09  4995.9 1983.59
  4999.4 1983.59  4999.7 1984.09  5029.9 1984.78  5049.9 1986.07  5079.9 1989.44
  5089.9 1989.88  5129.9 1988.52  5149.9 1987.33  5169.9 1985.22  5189.9 1984.47
  5239.9 1986.96  5259.9 1988.81  5330.0 1991.62  5420.0 1992.14  5451.2 1991.86
#Mann=3,-1,0
  4689.4    0.05       0  4995.7    0.05       0  4999.7    0.05       0
Bank Sta=4995.7,4999.7
Exp/Cntr=0.3,0.1

Type RM Length L Ch R = 1,1567,214,214,214
BEGIN DESCRIPTION:
Elm 01 72 1566.87
END DESCRIPTION:
XS GIS Cut Line= 3
      1565274.24      6775474.33      1565254.70      6775181.32
      1565185.97      6774841.56
#Sta/Elev= 30
  4707.6 1987.26  4754.0 1987.35  4775.2 1987.77  4874.3 1986.68  4904.4 1984.91
  4920.5 1984.31  4925.5 1983.34  4944.5 1982.64  4964.5 1981.29  4982.5 1981.15
  4982.8 1980.65  4986.3 1980.65  4986.5 1981.15  5000.4 1981.39  5035.3 1981.27
  5045.5 1982.02  5055.7 1981.47  5078.3 1982.44  5116.9 1985.42  5188.3 1987.45
  5198.5 1987.30  5208.7 1987.66  5218.9 1987.49  5225.4 1986.95  5230.5 1987.43
  5239.3 1987.63  5269.9 1987.60  5290.3 1988.02  5320.9 1987.68  5347.9 1988.00
#Mann=3,-1,0
  4707.6    0.05       0  4982.5    0.05       0  4986.5    0.05       0
Bank Sta=4982.5,4986.5
Exp/Cntr=0.3,0.1

Type RM Length L Ch R = 1,1353,208,208,208
BEGIN DESCRIPTION:
Elm 01 72 1353.36
END DESCRIPTION:
XS GIS Cut Line= 3
      1565445.85      6775400.77      1565453.66      6775136.87
      1565431.96      6774894.65
#Sta/Elev= 30
  4736.5 1982.88  4799.3 1982.76  4829.3 1982.38  4839.3 1982.39  4859.3 1982.02
  4869.3 1982.11  4880.6 1981.51  4899.3 1981.46  4959.4 1978.62  4979.4 1978.09
  4995.4 1977.99  4995.7 1977.49  4999.2 1977.49  4999.4 1977.99  5029.5 1978.03
  5043.0 1978.49  5049.6 1978.14  5069.7 1978.20  5079.7 1978.03  5089.7 1978.17
  5109.8 1979.21  5119.9 1979.16  5139.9 1980.24  5149.3 1981.01  5154.3 1980.81
  5170.1 1982.05  5180.1 1981.86  5190.1 1982.08  5210.2 1982.06  5243.7 1982.28
#Mann=3,-1,0
  4736.5    0.05       0  4995.4    0.05       0  4999.4    0.05       0
Bank Sta=4995.4,4999.4
Exp/Cntr=0.3,0.1

Type RM Length L Ch R = 1,1145,174,174,174
BEGIN DESCRIPTION:
Elm 01 72 1144.56
END DESCRIPTION:
XS GIS Cut Line= 3
      1565584.20      6775373.06      1565638.46      6775122.39
      1565629.80      6774721.96
#Sta/Elev= 30
  4743.6 1980.10  4759.0 1979.63  4767.6 1979.80  4772.7 1979.35  4830.6 1979.23
  4866.0 1977.51  4892.0 1978.00  4902.3 1977.83  4915.2 1976.56  4922.7 1976.49
  4932.9 1975.66  5022.5 1975.48  5022.7 1974.98  5026.2 1974.98  5026.5 1975.48
  5064.5 1976.28  5084.5 1977.15  5134.5 1976.68  5144.5 1976.06  5154.5 1976.19
  5164.5 1975.76  5184.5 1976.70  5214.5 1977.24  5234.5 1977.25  5254.5 1976.62
  5284.5 1976.63  5294.5 1976.83  5304.5 1977.82  5334.5 1979.03  5400.6 1980.67
#Mann=3,-1,0
  4743.6    0.05       0  5022.5    0.05       0  5026.5    0.05       0
Bank Sta=5022.5,5026.5
Exp/Cntr=0.3,0.1

Type RM Length L Ch R = 1,971,81,81,81
BEGIN DESCRIPTION:
Elm 01 72 971.24
END DESCRIPTION:
XS GIS Cut Line= 3
      1565766.85      6775342.21      1565766.85      6775186.83
      1565759.04      6774825.69
#Sta/Elev= 30
  4845.0 1978.20  4859.2 1978.12  4919.2 1976.57  4939.2 1975.66  4979.2 1973.27
  4989.2 1973.23  4997.3 1973.88  5029.2 1974.22  5049.2 1973.15  5077.2 1972.57
  5077.5 1972.07  5081.0 1972.07  5081.2 1972.57  5099.2 1973.06  5129.2 1973.26
  5139.2 1973.79  5159.2 1974.03  5169.2 1974.43  5179.2 1974.18  5189.2 1973.02
  5199.3 1972.60  5229.3 1972.67  5259.3 1973.51  5269.3 1974.16  5289.3 1976.10
  5309.3 1976.05  5320.8 1976.31  5349.3 1977.26  5357.9 1977.99  5361.6 1977.99
#Mann=3,-1,0
  4845.0    0.05       0  5077.2    0.05       0  5081.2    0.05       0
Bank Sta=5077.2,5081.2
Exp/Cntr=0.3,0.1

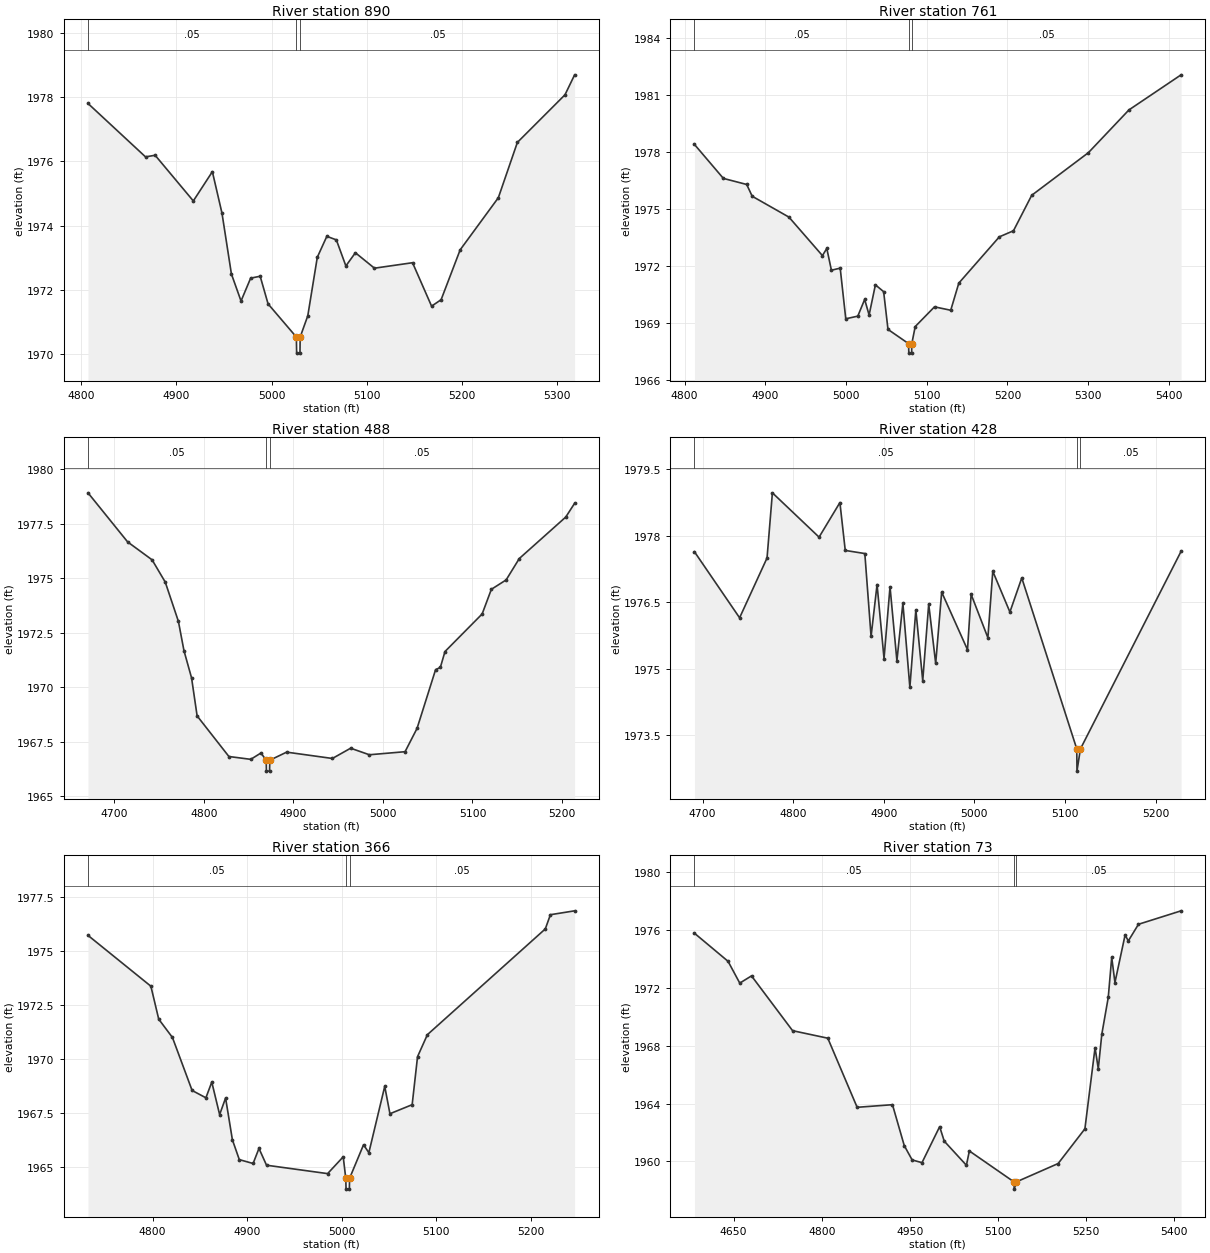
Type RM Length L Ch R = 1,890,129,129,129
BEGIN DESCRIPTION:
Elm 01 72 890.48
END DESCRIPTION:
XS GIS Cut Line= 3
      1565851.92      6775348.25      1565837.17      6775156.45
      1565831.96      6774837.86
#Sta/Elev= 30
  4807.3 1977.80  4867.7 1976.14  4877.8 1976.19  4917.9 1974.77  4937.9 1975.68
  4948.0 1974.39  4957.9 1972.50  4968.0 1971.66  4978.1 1972.37  4988.1 1972.43
  4996.4 1971.57  5026.1 1970.54  5026.4 1970.04  5029.9 1970.04  5030.1 1970.54
  5038.1 1971.20  5048.1 1973.02  5058.1 1973.67  5068.1 1973.56  5078.1 1972.75
  5088.1 1973.16  5108.1 1972.68  5148.1 1972.85  5168.1 1971.50  5178.1 1971.70
  5198.1 1973.25  5238.2 1974.87  5258.2 1976.59  5308.2 1978.07  5318.3 1978.69
#Mann=3,-1,0
  4807.3    0.05       0  5026.1    0.05       0  5030.1    0.05       0
Bank Sta=5026.1,5030.1
Exp/Cntr=0.3,0.1

Type RM Length L Ch R = 1,761,273,273,273
BEGIN DESCRIPTION:
Mapping XS ad3a4cb0
END DESCRIPTION:
XS GIS Cut Line= 3
      1565874.74      6775363.56      1565978.92      6775123.96
      1566006.70      6774783.66
#Sta/Elev= 30
  4812.3 1978.41  4848.1 1976.62  4877.0 1976.30  4883.8 1975.68  4929.3 1974.58
  4970.8 1972.55  4976.2 1972.93  4981.9 1971.78  4992.8 1971.89  4999.7 1969.22
  5014.6 1969.36  5023.1 1970.24  5028.6 1969.42  5036.4 1971.01  5046.6 1970.65
  5052.0 1968.66  5077.5 1967.91  5077.8 1967.41  5081.3 1967.41  5081.5 1967.91
  5085.7 1968.81  5109.6 1969.85  5129.7 1969.67  5139.7 1971.10  5189.9 1973.54
  5207.4 1973.86  5230.0 1975.73  5300.3 1977.98  5350.4 1980.23  5415.0 1982.08
#Mann=3,-1,0
  4812.3    0.05       0  5077.5    0.03       0  5081.5    0.05       0
Bank Sta=5077.5,5081.5
Exp/Cntr=0.3,0.1

Type RM Length L Ch R = 1,488,60,60,60
BEGIN DESCRIPTION:
Elm 01 72 487.6
END DESCRIPTION:
XS GIS Cut Line= 5
      1565889.16      6775383.01      1566032.39      6775278.84
      1566102.92      6775222.42      1566143.07      6775173.59
      1566200.29      6774968.46
#Sta/Elev= 30
  4670.5 1978.91  4714.8 1976.66  4742.1 1975.84  4756.8 1974.82  4771.5 1973.02
  4777.7 1971.68  4786.2 1970.43  4792.4 1968.69  4827.9 1966.83  4852.3 1966.70
  4863.7 1966.99  4869.6 1966.66  4869.8 1966.16  4873.3 1966.16  4873.6 1966.66
  4892.4 1967.03  4943.5 1966.74  4963.9 1967.21  4984.8 1966.91  5024.7 1967.05
  5038.1 1968.12  5058.8 1970.81  5064.1 1970.91  5069.3 1971.64  5110.8 1973.36
  5121.1 1974.49  5137.6 1974.92  5152.3 1975.90  5204.2 1977.80  5214.1 1978.43
#Mann=3,-1,0
  4670.5    0.05       0  4869.6    0.05       0  4873.6    0.05       0
Bank Sta=4869.6,4873.6
Exp/Cntr=0.3,0.1

Type RM Length L Ch R = 1,428,62,62,62
BEGIN DESCRIPTION:
Elm 01 72 428.01
END DESCRIPTION:
XS GIS Cut Line= 5
      1565953.16      6775416.66      1566084.48      6775332.01
      1566184.30      6775216.99      1566207.09      6775159.48
      1566251.57      6774998.93
#Sta/Elev= 30
  4691.1 1977.64  4740.9 1976.15  4771.2 1977.50  4777.1 1978.97  4828.6 1977.97
  4851.6 1978.75  4857.5 1977.67  4879.1 1977.60  4886.0 1975.73  4892.6 1976.90
  4900.3 1975.23  4906.9 1976.85  4914.5 1975.18  4921.1 1976.48  4928.8 1974.58
  4935.4 1976.33  4943.0 1974.73  4949.6 1976.46  4957.3 1975.12  4963.9 1976.73
  4992.4 1975.43  4996.4 1976.68  5014.9 1975.70  5020.3 1977.20  5039.2 1976.28
  5052.3 1977.05  5113.0 1973.19  5113.2 1972.69  5117.0 1973.19  5228.1 1977.65
#Mann=3,-1,0
  4691.1    0.05       0  5113.0    0.05       0  5117.0    0.05       0
Bank Sta=5113,5117
Exp/Cntr=0.3,0.1

Type RM Length L Ch R = 1,366,293,293,293
BEGIN DESCRIPTION:
Elm 01 72 366.06
END DESCRIPTION:
XS GIS Cut Line= 5
      1566033.48      6775440.52      1566187.56      6775323.33
      1566227.70      6775261.48      1566258.09      6775200.72
      1566306.93      6775028.15
#Sta/Elev= 30
  4731.6 1975.73  4798.1 1973.37  4806.4 1971.84  4820.9 1970.99  4841.7 1968.53
  4856.3 1968.19  4862.5 1968.92  4870.8 1967.41  4877.1 1968.18  4884.3 1966.24
  4891.6 1965.32  4906.2 1965.14  4912.4 1965.84  4920.4 1965.06  4985.0 1964.67
  5001.5 1965.45  5004.2 1964.45  5004.5 1963.95  5008.0 1963.95  5008.2 1964.45
  5023.0 1966.01  5028.6 1965.64  5045.4 1968.72  5050.9 1967.45  5074.4 1967.87
  5080.1 1970.10  5090.5 1971.12  5215.2 1976.03  5220.6 1976.69  5246.2 1976.87
#Mann=3,-1,0
  4731.6    0.05       0  5004.2    0.05       0  5008.2    0.05       0
Bank Sta=5004.2,5008.2
Exp/Cntr=0.3,0.1

Type RM Length L Ch R = 1,73,44,44,44
BEGIN DESCRIPTION:
Elm 01 72 73.35
END DESCRIPTION:
XS GIS Cut Line= 6
      1566037.79      6775452.45      1566335.13      6775450.28
      1566452.31      6775438.35      1566465.33      6775353.71
      1566460.99      6775239.78      1566369.91      6775045.67
#Sta/Elev= 30
  4583.2 1975.78  4640.4 1973.84  4660.4 1972.33  4680.4 1972.83  4750.4 1969.04
  4810.4 1968.52  4860.4 1963.74  4920.6 1963.92  4940.7 1961.09  4954.1 1960.10
  4970.9 1959.91  5001.0 1962.40  5008.8 1961.40  5046.6 1959.73  5051.6 1960.72
  5127.7 1958.58  5128.0 1958.08  5131.7 1958.58  5202.9 1959.85  5248.5 1962.25
  5265.8 1967.86  5271.3 1966.41  5277.3 1968.79  5288.3 1971.34  5294.2 1974.11
  5299.7 1972.37  5317.0 1975.66  5322.5 1975.25  5339.8 1976.40  5412.4 1977.33
#Mann=3,-1,0
  4583.2    0.05       0  5127.7    0.05       0  5131.7    0.05       0
Bank Sta=5127.7,5131.7
Exp/Cntr=0.3,0.1

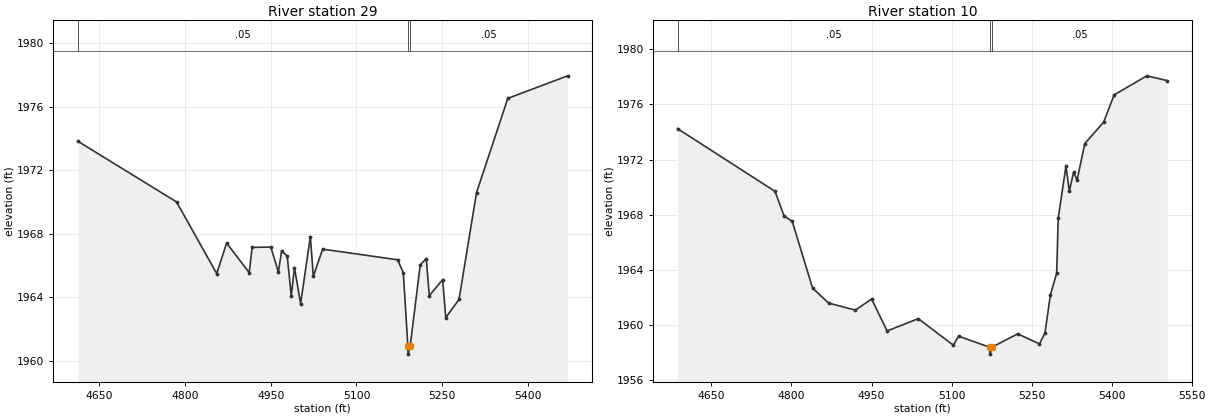
Type RM Length L Ch R = 1,29,19,19,19
BEGIN DESCRIPTION:
Elm 01 72 546.377
END DESCRIPTION:
XS GIS Cut Line= 6
      1566102.88      6775477.41      1566364.42      6775496.94
      1566483.99      6775467.45      1566503.31      6775393.86
      1566504.40      6775253.89      1566401.61      6775022.34
#Sta/Elev= 30
  4612.7 1973.82  4785.3 1970.00  4855.5 1965.49  4872.8 1967.41  4912.4 1965.55
  4917.4 1967.14  4950.2 1967.16  4963.4 1965.59  4969.0 1966.91  4978.8 1966.60
  4985.9 1964.09  4991.5 1965.86  5002.3 1963.60  5019.3 1967.82  5024.5 1965.32
  5040.8 1967.03  5171.9 1966.36  5181.9 1965.55  5189.9 1960.92  5190.2 1960.42
  5193.9 1960.92  5211.5 1966.03  5222.0 1966.44  5227.4 1964.10  5250.7 1965.11
  5256.2 1962.72  5279.4 1963.87  5310.0 1970.59  5364.7 1976.52  5469.4 1977.94
#Mann=3,-1,0
  4612.7    0.05       0  5189.9    0.05       0  5193.9    0.05       0
Bank Sta=5189.9,5193.9
Exp/Cntr=0.3,0.1

Type RM Length L Ch R = 1,10,0,0,0
BEGIN DESCRIPTION:
Elm 01 72 0.1
END DESCRIPTION:
XS GIS Cut Line= 6
      1566114.24      6775504.53      1566417.00      6775539.25
      1566460.40      6775533.83      1566513.57      6775458.96
      1566530.93      6775196.37      1566422.17      6775021.26
#Sta/Elev= 30
  4586.5 1974.24  4769.1 1969.70  4786.0 1967.92  4801.4 1967.52  4839.5 1962.69
  4869.5 1961.60  4919.7 1961.09  4950.2 1961.89  4979.2 1959.58  5037.7 1960.47
  5103.2 1958.55  5113.2 1959.20  5171.5 1958.40  5171.8 1957.90  5175.5 1958.40
  5224.0 1959.37  5264.8 1958.64  5275.0 1959.42  5285.2 1962.18  5297.0 1963.77
  5299.9 1967.74  5314.4 1971.53  5320.7 1969.70  5328.9 1971.12  5335.2 1970.49
  5349.7 1973.16  5385.0 1974.71  5404.7 1976.69  5465.9 1978.07  5504.4 1977.72
#Mann=3,-1,0
  4586.5    0.05       0  5171.5    0.05       0  5175.5    0.05       0
Bank Sta=5171.5,5175.5
Exp/Cntr=0.3,0.1

Chan Stop Cuts=-1