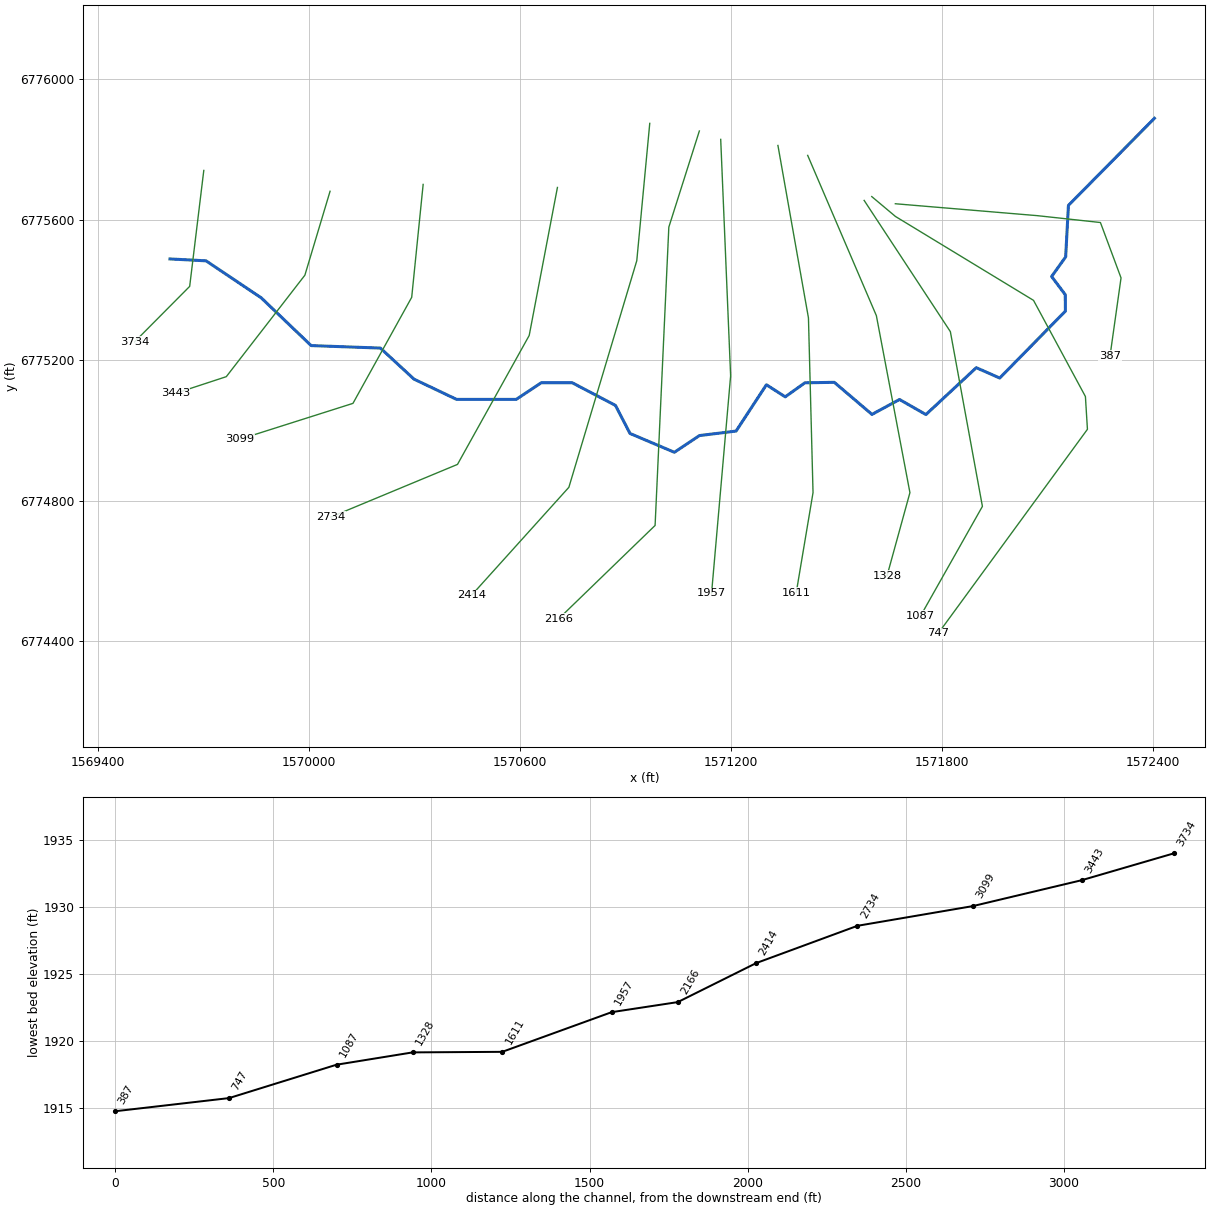
--- Elm 01 73.prj (project) ---

Proj Title=Elm 01 73 Base Level Engineering
Current Plan=p01
Default Exp/Contr=0.3,0.1
English Units
Geom File=g01
Flow File=f01
Plan File=p01
BEGIN DESCRIPTION:
Elm 01 73
END DESCRIPTION:

--- Elm 01 73.p01 (plan) ---

Plan Title=Multiple Run
Short Identifier=Multiple
Geom File=g01
Flow File=f01
Subcritical Flow
K Sum by GR= 0
Std Step Tol= 0.01
Critical Tol= 0.01
Num of Std Step Trials= 20
Max Error Tol= 0.3
Flow Tol Ratio= 0.001
Split Flow NTrial= 30
Split Flow Tol= 0.02
Split Flow Ratio= 0.02
Log Output Level= 0
Friction Slope Method= 1
Unsteady Friction Slope Method= 2
Unsteady Bridges Friction Slope Method= 1
Parabolic Critical Depth
Global Vel Dist=  1 , 1 , 1
Global Log Level= 0
CheckData=True
Encroach Param= -1, 0, 0, 0
BEGIN DESCRIPTION:
Multiple Run
END DESCRIPTION:

--- Elm 01 73.f01 (steady flow) ---

Flow Title=Multiple
Number of Profiles=7
Profile Names=10-year,25-year,50-year,1pct_min,100-year,1pct_plu,500-year
River Rch & RM= Elm 01 73,Reach-1,3734
     261     368     458     354     568     781     884
Boundary for River Rch & Prof#=Elm 01 73,Reach-1,1
Up Type=0
Dn Type=3
Dn Slope=0.001
Boundary for River Rch & Prof#=Elm 01 73,Reach-1,2
Up Type=0
Dn Type=3
Dn Slope=0.001
Boundary for River Rch & Prof#=Elm 01 73,Reach-1,3
Up Type=0
Dn Type=3
Dn Slope=0.001
Boundary for River Rch & Prof#=Elm 01 73,Reach-1,4
Up Type=0
Dn Type=3
Dn Slope=0.001
Boundary for River Rch & Prof#=Elm 01 73,Reach-1,5
Up Type=0
Dn Type=3
Dn Slope=0.001
Boundary for River Rch & Prof#=Elm 01 73,Reach-1,6
Up Type=0
Dn Type=3
Dn Slope=0.001
Boundary for River Rch & Prof#=Elm 01 73,Reach-1,7
Up Type=0
Dn Type=3
Dn Slope=0.001

--- Elm 01 73.g01 (geometry) ---

Geom Title=Existing Conditions

River Reach=Elm 01 73,Reach-1
Reach XY= 30
      1569605.00      6775488.00      1569707.49      6775482.64
      1569864.68      6775377.22      1570006.46      6775241.54
      1570203.53      6775234.45      1570298.95      6775146.16
      1570420.21      6775088.50      1570589.78      6775088.52
      1570660.98      6775135.83      1570749.04      6775135.86
      1570872.02      6775071.43      1570913.49      6774991.53
      1571039.60      6774938.08      1571110.97      6774985.61
      1571215.10      6774998.39      1571301.42      6775130.11
      1571354.89      6775095.81      1571410.89      6775135.65
      1571494.52      6775137.05      1571601.60      6775045.83
      1571680.00      6775088.21      1571755.09      6775045.35
      1571898.33      6775178.70      1571965.00      6775149.24
      1572151.84      6775339.65      1572151.43      6775386.35
      1572112.59      6775437.99      1572152.53      6775493.86
      1572160.47      6775640.45      1572405.00      6775888.00

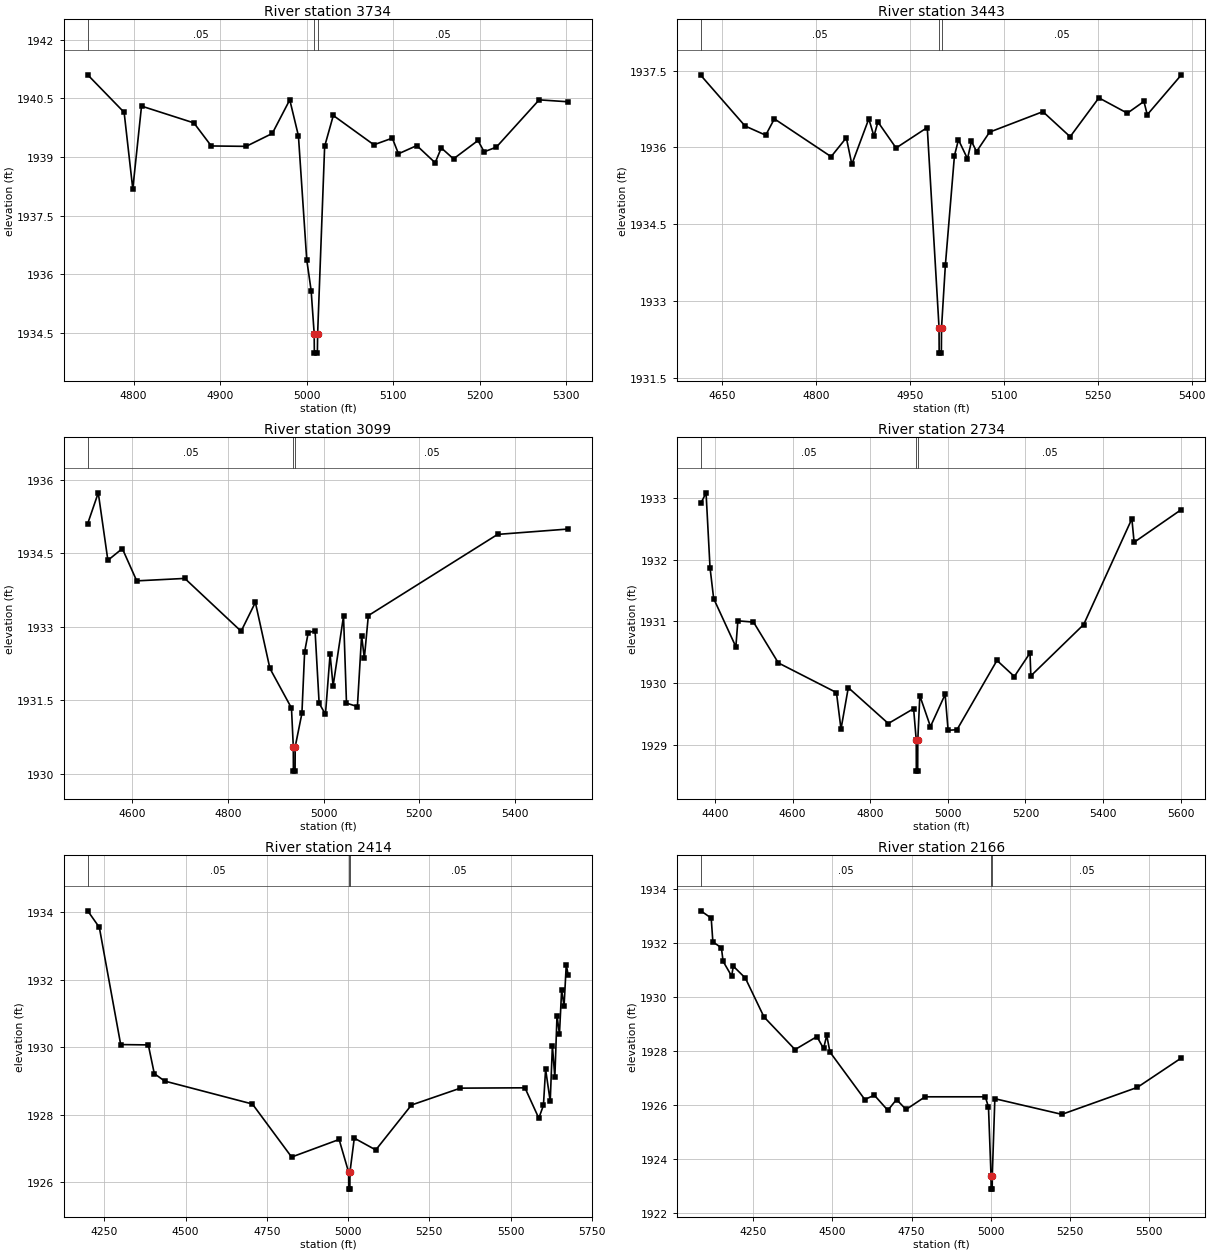
Type RM Length L Ch R = 1,3734,291,291,291
BEGIN DESCRIPTION:
Elm 01 73 2.0
END DESCRIPTION:
XS GIS Cut Line= 3
      1569701.13      6775739.76      1569660.99      6775409.95
      1569503.81      6775251.69
#Sta/Elev= 30
  4746.9 1941.10  4789.0 1940.14  4799.0 1938.18  4809.1 1940.30  4869.6 1939.87
  4889.7 1939.28  4930.0 1939.27  4960.2 1939.60  4980.4 1940.46  4990.4 1939.54
  5000.0 1936.37  5005.1 1935.58  5008.6 1934.48  5008.8 1933.98  5012.3 1933.98
  5012.6 1934.48  5020.7 1939.27  5030.7 1940.06  5077.6 1939.31  5098.9 1939.48
  5106.0 1939.08  5127.2 1939.29  5148.4 1938.85  5155.5 1939.23  5169.6 1938.95
  5197.9 1939.42  5205.0 1939.13  5219.1 1939.25  5268.6 1940.46  5302.2 1940.41
#Mann=3,-1,0
  4746.9    0.05       0  5008.6    0.05       0  5012.6    0.05       0
Bank Sta=5008.6,5012.6
Exp/Cntr=0.3,0.1

Type RM Length L Ch R = 1,3443,344,344,344
BEGIN DESCRIPTION:
Mapping XS 3bdebb5e
END DESCRIPTION:
XS GIS Cut Line= 4
      1570060.30      6775680.49      1569988.68      6775441.78
      1569765.16      6775153.15      1569619.88      6775105.44
#Sta/Elev= 30
  4616.5 1937.41  4687.1 1936.42  4720.1 1936.24  4733.9 1936.56  4824.5 1935.82
  4848.8 1936.19  4857.6 1935.67  4884.7 1936.56  4892.9 1936.22  4899.2 1936.50
  4928.2 1935.99  4978.0 1936.39  4996.8 1932.48  4997.0 1931.98  5000.5 1931.98
  5000.8 1932.48  5006.9 1933.70  5021.4 1935.84  5027.8 1936.15  5042.2 1935.78
  5048.6 1936.12  5056.7 1935.92  5077.5 1936.30  5162.6 1936.70  5206.1 1936.21
  5252.0 1936.97  5297.4 1936.67  5323.9 1936.90  5329.2 1936.64  5383.7 1937.42
#Mann=3,-1,0
  4616.5    0.05       0  4996.8    0.05       0  5000.8    0.05       0
Bank Sta=4996.8,5000.8
Exp/Cntr=0.3,0.1

Type RM Length L Ch R = 1,3099,365,365,365
BEGIN DESCRIPTION:
Mapping XS a929ac29
END DESCRIPTION:
XS GIS Cut Line= 4
      1570325.05      6775700.00      1570292.50      6775378.84
      1570125.40      6775077.19      1569804.26      6774975.21
#Sta/Elev= 30
  4506.9 1935.11  4529.0 1935.74  4549.1 1934.36  4579.3 1934.60  4609.4 1933.94
  4709.9 1933.99  4827.6 1932.91  4857.4 1933.50  4887.8 1932.15  4932.9 1931.34
  4936.7 1930.55  4936.9 1930.05  4940.4 1930.05  4940.7 1930.55  4954.7 1931.23
  4960.4 1932.49  4967.9 1932.88  4982.2 1932.92  4990.7 1931.44  5003.9 1931.21
  5013.6 1932.44  5019.9 1931.79  5041.7 1933.22  5047.9 1931.44  5070.7 1931.37
  5079.5 1932.82  5085.2 1932.36  5093.6 1933.23  5363.8 1934.89  5511.5 1935.00
#Mann=3,-1,0
  4506.9    0.05       0  4936.7    0.05       0  4940.7    0.05       0
Bank Sta=4936.7,4940.7
Exp/Cntr=0.3,0.1

Type RM Length L Ch R = 1,2734,320,320,320
BEGIN DESCRIPTION:
Mapping XS 74263d82
END DESCRIPTION:
XS GIS Cut Line= 4
      1570706.99      6775691.30      1570626.70      6775270.33
      1570422.71      6774903.58      1570062.51      6774753.86
#Sta/Elev= 30
  4363.4 1932.91  4376.9 1933.08  4387.1 1931.87  4396.5 1931.37  4453.7 1930.59
  4458.8 1931.01  4499.1 1930.99  4563.1 1930.33  4712.9 1929.85  4724.6 1929.26
  4743.4 1929.93  4846.5 1929.35  4911.7 1929.59  4918.5 1929.08  4918.7 1928.58
  4922.2 1928.58  4922.5 1929.08  4927.7 1929.80  4955.1 1929.30  4992.9 1929.82
  5000.6 1929.24  5023.5 1929.25  5126.5 1930.37  5171.3 1930.11  5211.6 1930.49
  5213.8 1930.12  5349.9 1930.95  5474.1 1932.66  5479.9 1932.28  5601.7 1932.81
#Mann=3,-1,0
  4363.4    0.05       0  4918.5    0.05       0  4922.5    0.05       0
Bank Sta=4918.5,4922.5
Exp/Cntr=0.3,0.1

Type RM Length L Ch R = 1,2414,248,248,248
BEGIN DESCRIPTION:
Mapping XS 1a6ccf0e
END DESCRIPTION:
XS GIS Cut Line= 4
      1570969.59      6775873.63      1570932.69      6775483.01
      1570739.55      6774838.48      1570462.97      6774531.65
#Sta/Elev= 30
  4199.1 1934.04  4234.9 1933.55  4300.6 1930.08  4385.6 1930.07  4404.0 1929.22
  4435.8 1929.00  4705.8 1928.32  4826.4 1926.75  4972.5 1927.27  5001.8 1926.30
  5002.1 1925.80  5005.6 1925.80  5005.8 1926.30  5019.2 1927.31  5085.3 1926.96
  5195.0 1928.29  5345.7 1928.79  5544.2 1928.80  5586.8 1927.90  5601.0 1928.28
  5607.7 1929.35  5621.9 1928.40  5628.6 1930.05  5636.1 1929.11  5642.8 1930.94
  5650.3 1930.39  5657.0 1931.69  5664.5 1931.22  5671.2 1932.44  5677.4 1932.13
#Mann=3,-1,0
  4199.1    0.05       0  5001.8    0.05       0  5005.8    0.05       0
Bank Sta=5001.8,5005.8
Exp/Cntr=0.3,0.1

Type RM Length L Ch R = 1,2166,209,209,209
BEGIN DESCRIPTION:
Mapping XS 0de35b00
END DESCRIPTION:
XS GIS Cut Line= 4
      1571110.64      6775851.93      1571023.84      6775578.49
      1570984.78      6774729.97      1570711.35      6774465.22
#Sta/Elev= 30
  4084.8 1933.20  4117.6 1932.93  4122.8 1932.05  4149.8 1931.83  4155.1 1931.33
  4182.1 1930.78  4187.3 1931.15  4225.3 1930.71  4284.1 1929.27  4382.2 1928.06
  4451.2 1928.54  4472.3 1928.10  4482.3 1928.59  4492.3 1927.97  4602.4 1926.21
  4632.5 1926.37  4675.1 1925.81  4702.5 1926.21  4732.6 1925.84  4792.6 1926.31
  4982.8 1926.31  4992.8 1925.93  5000.8 1923.39  5001.1 1922.89  5004.6 1922.89
  5004.8 1923.39  5012.9 1926.24  5224.4 1925.66  5462.8 1926.66  5601.7 1927.75
#Mann=3,-1,0
  4084.8    0.05       0  5000.8    0.05       0  5004.8    0.05       0
Bank Sta=5000.8,5004.8
Exp/Cntr=0.3,0.1

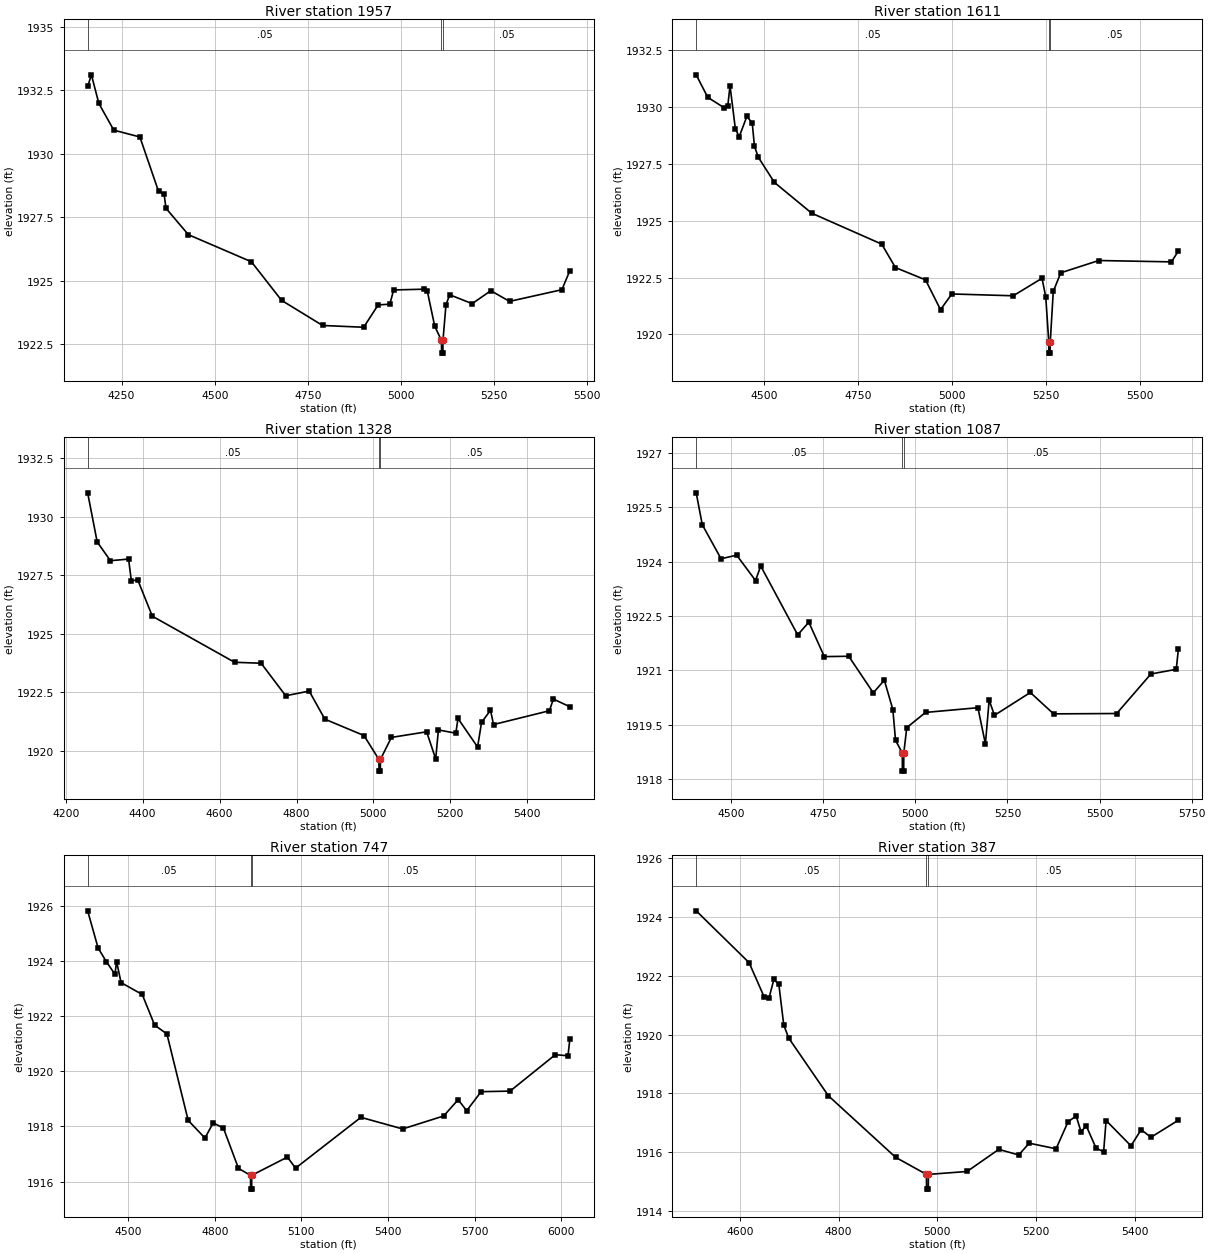
Type RM Length L Ch R = 1,1957,346,346,346
BEGIN DESCRIPTION:
Mapping XS bbd877fa
END DESCRIPTION:
XS GIS Cut Line= 3
      1571171.41      6775828.06      1571199.62      6775155.32
      1571145.37      6774536.82
#Sta/Elev= 30
  4159.0 1932.65  4169.1 1933.11  4189.1 1931.98  4229.1 1930.93  4299.2 1930.66
  4349.2 1928.52  4364.1 1928.42  4369.2 1927.85  4429.3 1926.81  4598.6 1925.74
  4679.5 1924.22  4789.6 1923.23  4899.9 1923.16  4938.7 1924.04  4970.2 1924.07
  4980.2 1924.63  5061.2 1924.66  5070.6 1924.59  5090.6 1923.20  5108.7 1922.64
  5109.0 1922.14  5112.5 1922.14  5112.7 1922.64  5120.8 1924.05  5130.8 1924.44
  5191.0 1924.09  5241.2 1924.60  5291.4 1924.18  5431.9 1924.64  5453.2 1925.39
#Mann=3,-1,0
  4159.0    0.05       0  5108.7    0.03       0  5112.7    0.05       0
Bank Sta=5108.7,5112.7
Exp/Cntr=0.3,0.1

Type RM Length L Ch R = 1,1611,283,283,283
BEGIN DESCRIPTION:
Mapping XS 10c8ff4b
END DESCRIPTION:
XS GIS Cut Line= 4
      1571334.17      6775810.71      1571420.98      6775320.25
      1571434.00      6774823.29      1571386.25      6774538.99
#Sta/Elev= 30
  4318.8 1931.41  4349.6 1930.42  4392.6 1929.97  4402.8 1930.03  4408.8 1930.93
  4423.1 1929.03  4433.3 1928.69  4453.6 1929.58  4467.9 1929.30  4473.9 1928.27
  4484.0 1927.79  4527.1 1926.68  4626.2 1925.33  4812.7 1923.97  4849.1 1922.94
  4929.2 1922.40  4969.2 1921.09  4999.2 1921.78  5162.8 1921.70  5239.3 1922.47
  5249.3 1921.65  5257.3 1919.68  5257.5 1919.18  5261.0 1919.18  5261.3 1919.68
  5269.3 1921.89  5289.3 1922.71  5390.4 1923.25  5583.9 1923.19  5602.3 1923.67
#Mann=3,-1,0
  4318.8    0.05       0  5257.3    0.05       0  5261.3    0.05       0
Bank Sta=5257.3,5261.3
Exp/Cntr=0.3,0.1

Type RM Length L Ch R = 1,1328,241,241,241
BEGIN DESCRIPTION:
Mapping XS 5d6b8fc4
END DESCRIPTION:
XS GIS Cut Line= 4
      1571418.80      6775782.51      1571614.12      6775326.76
      1571709.60      6774823.29      1571644.51      6774586.77
#Sta/Elev= 30
  4257.0 1931.03  4281.8 1928.93  4316.3 1928.13  4363.4 1928.20  4370.7 1927.26
  4387.0 1927.32  4425.1 1925.76  4639.0 1923.79  4708.0 1923.75  4771.9 1922.36
  4833.0 1922.56  4873.7 1921.36  4975.5 1920.66  5014.2 1919.64  5014.5 1919.14
  5018.0 1919.14  5018.2 1919.64  5046.7 1920.58  5138.3 1920.82  5161.9 1919.66
  5168.9 1920.90  5214.2 1920.76  5219.8 1921.39  5270.8 1920.17  5281.1 1921.22
  5304.3 1921.74  5312.3 1921.13  5457.5 1921.72  5467.8 1922.22  5510.6 1921.89
#Mann=3,-1,0
  4257.0    0.05       0  5014.2    0.05       0  5018.2    0.05       0
Bank Sta=5014.2,5018.2
Exp/Cntr=0.3,0.1

Type RM Length L Ch R = 1,1087,340,340,340
BEGIN DESCRIPTION:
Mapping XS f6bd6094
END DESCRIPTION:
XS GIS Cut Line= 4
      1571579.41      6775654.43      1571824.62      6775281.19
      1571915.77      6774784.22      1571740.05      6774472.93
#Sta/Elev= 30
  4404.7 1925.90  4421.2 1925.02  4472.2 1924.08  4514.6 1924.18  4565.8 1923.48
  4579.9 1923.88  4680.3 1921.98  4710.5 1922.33  4752.6 1921.38  4818.9 1921.39
  4885.6 1920.38  4915.5 1920.73  4938.7 1919.92  4946.0 1919.07  4964.4 1918.72
  4964.6 1918.22  4968.1 1918.22  4968.4 1918.72  4976.5 1919.42  5027.4 1919.84
  5169.7 1919.97  5190.0 1918.97  5200.2 1920.18  5214.6 1919.76  5312.0 1920.39
  5375.2 1919.80  5546.5 1919.81  5639.3 1920.90  5708.2 1921.03  5714.0 1921.58
#Mann=3,-1,0
  4404.7    0.05       0  4964.4    0.03       0  4968.4    0.05       0
Bank Sta=4964.4,4968.4
Exp/Cntr=0.3,0.1

Type RM Length L Ch R = 1,747,360,360,360
BEGIN DESCRIPTION:
Mapping XS 9c0f6035
END DESCRIPTION:
XS GIS Cut Line= 6
      1571601.06      6775665.33      1571668.37      6775608.88
      1572061.17      6775370.16      1572208.74      6775096.72
      1572214.48      6775003.43      1571790.08      6774422.90
#Sta/Elev= 30
  4359.2 1925.81  4395.5 1924.46  4424.1 1923.97  4453.7 1923.51  4459.5 1923.97
  4475.0 1923.21  4548.4 1922.78  4591.3 1921.67  4633.9 1921.35  4707.5 1918.22
  4765.7 1917.58  4794.2 1918.13  4829.7 1917.94  4881.9 1916.48  4923.7 1916.23
  4924.0 1915.73  4927.5 1915.73  4927.7 1916.23  5051.4 1916.89  5079.6 1916.49
  5306.1 1918.33  5450.8 1917.91  5592.9 1918.38  5643.1 1918.97  5672.5 1918.57
  5722.7 1919.26  5823.0 1919.28  5979.8 1920.60  6023.7 1920.56  6030.0 1921.16
#Mann=3,-1,0
  4359.2    0.05       0  4923.7    0.05       0  4927.7    0.05       0
Bank Sta=4923.7,4927.7
Exp/Cntr=0.3,0.1

Type RM Length L Ch R = 1,387,0,0,0
BEGIN DESCRIPTION:
Elm 01 73 1.0
END DESCRIPTION:
XS GIS Cut Line= 5
      1571668.13      6775644.97      1572071.78      6775611.12
      1572251.47      6775591.59      1572310.06      6775434.04
      1572278.84      6775212.84
#Sta/Elev= 30
  4511.2 1924.20  4618.4 1922.44  4648.6 1921.29  4659.0 1921.25  4668.6 1921.87
  4678.7 1921.70  4688.7 1920.32  4698.7 1919.88  4779.1 1917.92  4915.4 1915.83
  4977.9 1915.25  4978.1 1914.75  4981.6 1914.75  4981.9 1915.25  5060.3 1915.35
  5124.5 1916.10  5164.9 1915.91  5186.2 1916.31  5240.6 1916.12  5265.0 1917.04
  5281.3 1917.23  5291.4 1916.69  5301.5 1916.91  5321.7 1916.14  5337.0 1916.02
  5342.0 1917.08  5392.4 1916.22  5413.1 1916.77  5432.8 1916.51  5488.5 1917.09
#Mann=3,-1,0
  4511.2    0.05       0  4977.9    0.03       0  4981.9    0.05       0
Bank Sta=4977.9,4981.9
Exp/Cntr=0.3,0.1

Chan Stop Cuts=-1