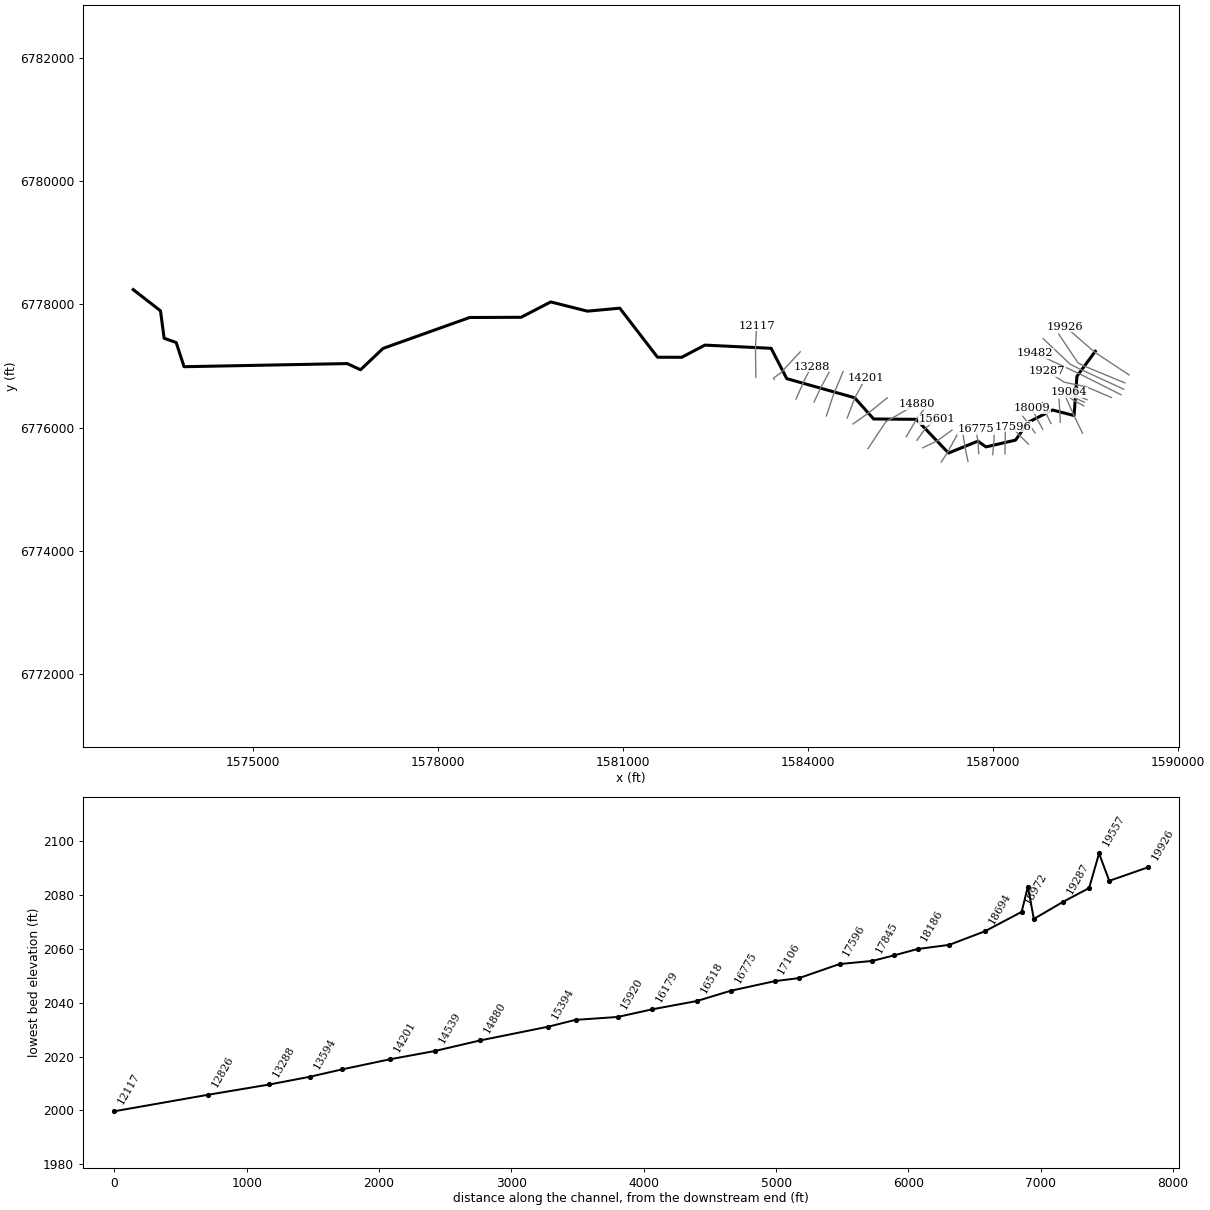
--- Elm 01 74.prj (project) ---

Proj Title=Elm 01 74 Base Level Engineering
Current Plan=p01
Default Exp/Contr=0.3,0.1
English Units
Geom File=g01
Flow File=f01
Plan File=p01
BEGIN DESCRIPTION:
Elm 01 74
END DESCRIPTION:

--- Elm 01 74.p01 (plan) ---

Plan Title=Multiple Run
Short Identifier=Multiple
Geom File=g01
Flow File=f01
Subcritical Flow
K Sum by GR= 0
Std Step Tol= 0.01
Critical Tol= 0.01
Num of Std Step Trials= 20
Max Error Tol= 0.3
Flow Tol Ratio= 0.001
Split Flow NTrial= 30
Split Flow Tol= 0.02
Split Flow Ratio= 0.02
Log Output Level= 0
Friction Slope Method= 1
Unsteady Friction Slope Method= 2
Unsteady Bridges Friction Slope Method= 1
Parabolic Critical Depth
Global Vel Dist=  1 , 1 , 1
Global Log Level= 0
CheckData=True
Encroach Param= -1, 0, 0, 0
BEGIN DESCRIPTION:
Multiple Run
END DESCRIPTION:

--- Elm 01 74.f01 (steady flow) ---

Flow Title=Multiple
Number of Profiles=7
Profile Names=10-year,25-year,50-year,1pct_min,100-year,1pct_plu,500-year
River Rch & RM= Elm 01 74,Reach-1,19926
     346     500     633     498     798    1100    1290
River Rch & RM= Elm 01 74,Reach-1,18009
     477     694     884     697    1120    1540    1810
River Rch & RM= Elm 01 74,Reach-1,8170
     525     766     975     769    1230    1700    1990
Boundary for River Rch & Prof#=Elm 01 74,Reach-1,1
Up Type=0
Dn Type=3
Dn Slope=0.001
Boundary for River Rch & Prof#=Elm 01 74,Reach-1,2
Up Type=0
Dn Type=3
Dn Slope=0.001
Boundary for River Rch & Prof#=Elm 01 74,Reach-1,3
Up Type=0
Dn Type=3
Dn Slope=0.001
Boundary for River Rch & Prof#=Elm 01 74,Reach-1,4
Up Type=0
Dn Type=3
Dn Slope=0.001
Boundary for River Rch & Prof#=Elm 01 74,Reach-1,5
Up Type=0
Dn Type=3
Dn Slope=0.001
Boundary for River Rch & Prof#=Elm 01 74,Reach-1,6
Up Type=0
Dn Type=3
Dn Slope=0.001
Boundary for River Rch & Prof#=Elm 01 74,Reach-1,7
Up Type=0
Dn Type=3
Dn Slope=0.001

--- Elm 01 74.g01 (geometry) ---

Geom Title=Existing Conditions

River Reach=Elm 01 74,Reach-1
Reach XY= 30
      1588655.00      6777238.00      1588357.23      6776832.07
      1588311.51      6776195.62      1587960.93      6776285.77
      1587560.61      6776082.41      1587362.01      6775797.03
      1586882.20      6775687.44      1586751.66      6775780.40
      1586275.05      6775587.80      1585753.54      6776134.46
      1585060.86      6776140.07      1584753.54      6776484.46
      1583652.69      6776793.82      1583399.16      6777285.95
      1582324.98      6777338.04      1581949.48      6777140.35
      1581556.46      6777141.54      1580944.57      6777936.95
      1580420.16      6777888.39      1579825.21      6778038.21
      1579344.56      6777789.05      1578510.94      6777785.74
      1577106.47      6777284.45      1576740.96      6776938.09
      1576525.15      6777038.37      1573879.78      6776987.67
      1573751.69      6777379.98      1573556.28      6777449.03
      1573497.52      6777894.06      1573055.00      6778238.00

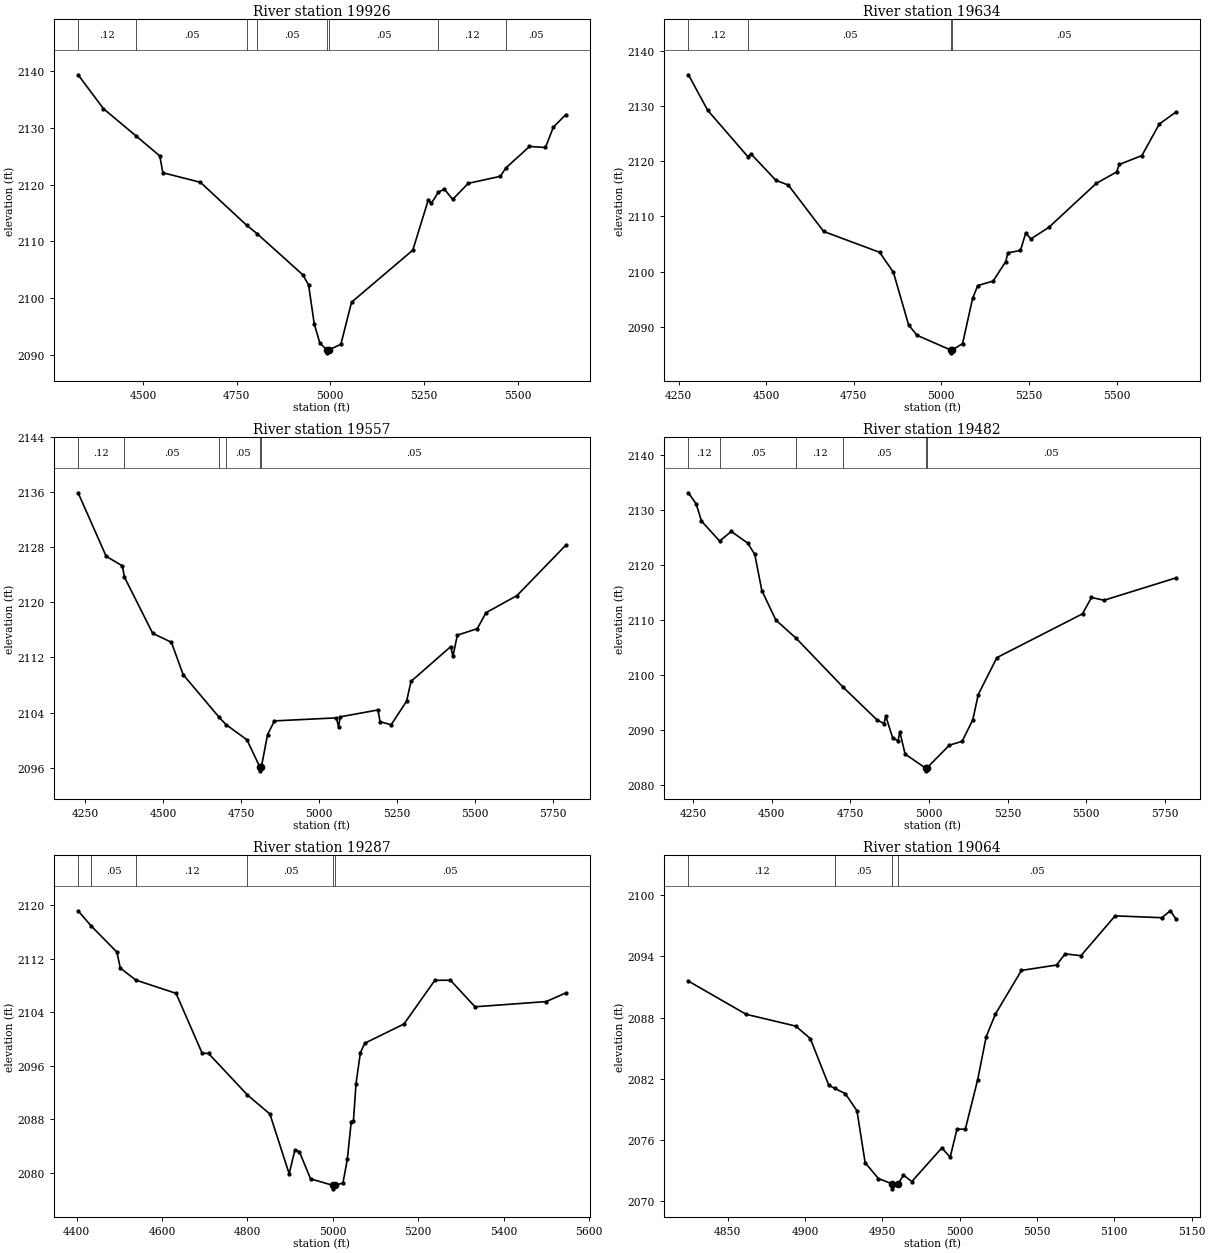
Type RM Length L Ch R = 1,19926,292,292,292
BEGIN DESCRIPTION:
Elm 01 74 19642.71
END DESCRIPTION:
XS GIS Cut Line= 3
      1589203.47      6776853.74      1588642.41      6777225.60
      1588168.56      6777637.12
#Sta/Elev= 30
  4326.9 2139.41  4394.5 2133.43  4482.7 2128.55  4544.9 2125.09  4553.0 2122.12
  4653.2 2120.44  4776.8 2112.85  4804.2 2111.39  4926.9 2104.09  4942.0 2102.31
  4957.0 2095.45  4972.0 2092.07  4991.1 2090.84  4991.3 2090.34  4995.1 2090.84
  5028.1 2091.84  5056.6 2099.28  5220.0 2108.46  5261.7 2117.40  5269.3 2116.70
  5288.5 2118.71  5304.4 2119.22  5326.3 2117.42  5368.1 2120.25  5453.5 2121.49
  5468.2 2122.95  5531.4 2126.76  5574.1 2126.58  5595.0 2130.16  5627.6 2132.34
#Mann=8,-1,0
  4326.9    0.12       0  4482.7    0.05       0  4776.8    0.12       0
  4804.2    0.05       0  4991.1    0.05       0  4995.1    0.05       0
  5288.5    0.12       0  5468.2    0.05       0
Bank Sta=4991.1,4995.1
Exp/Cntr=0.3,0.1

Type RM Length L Ch R = 1,19634,77,77,77
BEGIN DESCRIPTION:
Elm 01 74 19634.42
END DESCRIPTION:
XS GIS Cut Line= 4
      1589135.81      6776725.23      1588467.39      6777001.28
      1588373.64      6777051.63      1588061.15      6777518.63
#Sta/Elev= 30
  4278.0 2135.61  4333.0 2129.18  4447.9 2120.78  4456.5 2121.31  4527.7 2116.52
  4563.0 2115.67  4664.0 2107.27  4823.8 2103.50  4863.1 2099.89  4906.4 2090.39
  4930.3 2088.50  5027.1 2085.82  5027.4 2085.32  5031.1 2085.82  5060.6 2087.00
  5089.2 2095.17  5104.0 2097.49  5147.7 2098.30  5183.8 2101.82  5189.8 2103.40
  5225.8 2103.84  5240.8 2106.96  5255.8 2105.93  5306.9 2108.02  5442.0 2115.96
  5500.3 2118.03  5508.0 2119.39  5572.5 2121.00  5622.1 2126.70  5669.5 2128.86
#Mann=4,-1,0
  4278.0    0.12       0  4447.9    0.05       0  5027.1    0.05       0
  5031.1    0.05       0
Bank Sta=5027.1,5031.1
Exp/Cntr=0.3,0.1

Type RM Length L Ch R = 1,19557,75,75,75
BEGIN DESCRIPTION:
Elm 01 74 19556.99
END DESCRIPTION:
XS GIS Cut Line= 4
      1589116.70      6776622.81      1588410.10      6776947.46
      1588253.85      6777023.85      1587809.34      6777442.41
#Sta/Elev= 30
  4227.3 2135.94  4317.2 2126.71  4369.1 2125.32  4375.8 2123.68  4466.5 2115.50
  4526.3 2114.21  4564.0 2109.50  4677.9 2103.38  4701.1 2102.25  4768.4 2100.03
  4810.4 2096.02  4810.7 2095.52  4814.4 2096.02  4834.4 2100.78  4856.5 2102.78
  5055.1 2103.22  5061.9 2101.92  5067.4 2103.37  5188.2 2104.37  5195.0 2102.66
  5230.6 2102.22  5280.0 2105.65  5294.2 2108.52  5421.6 2113.59  5428.5 2112.15
  5442.6 2115.24  5506.6 2116.19  5534.5 2118.51  5633.6 2120.99  5789.4 2128.28
#Mann=6,-1,0
  4227.3    0.12       0  4375.8    0.05       0  4677.9    0.12       0
  4701.1    0.05       0  4810.4    0.05       0  4814.4    0.05       0
Bank Sta=4810.4,4814.4
Exp/Cntr=0.3,0.1

Type RM Length L Ch R = 1,19482,195,195,195
BEGIN DESCRIPTION:
Elm 01 74 19482.41
END DESCRIPTION:
XS GIS Cut Line= 4
      1589073.27      6776532.54      1588387.53      6776878.01
      1588222.60      6776954.40      1587679.58      6777207.70
#Sta/Elev= 30
  4235.7 2133.21  4260.4 2131.17  4277.1 2128.07  4334.8 2124.43  4371.9 2126.18
  4424.1 2124.05  4446.5 2122.00  4468.9 2115.43  4513.7 2110.04  4577.7 2106.77
  4726.7 2097.89  4834.8 2091.92  4857.1 2091.23  4862.7 2092.61  4885.0 2088.56
  4901.8 2088.15  4907.4 2089.74  4924.1 2085.70  4989.0 2083.15  4989.2 2082.65
  4993.0 2083.15  5065.0 2087.33  5105.3 2088.01  5139.2 2091.92  5156.6 2096.53
  5215.8 2103.24  5487.8 2111.20  5516.2 2114.17  5556.4 2113.67  5784.5 2117.73
#Mann=6,-1,0
  4235.7    0.12       0  4334.8    0.05       0  4577.7    0.12       0
  4726.7    0.05       0  4989.0    0.05       0  4993.0    0.05       0
Bank Sta=4989,4993
Exp/Cntr=0.3,0.1

Type RM Length L Ch R = 1,19287,223,223,223
BEGIN DESCRIPTION:
Mapping XS 0756ffd4
END DESCRIPTION:
XS GIS Cut Line= 4
      1588915.88      6776488.33      1588510.02      6776661.96
      1588154.12      6776735.74      1587869.88      6776915.83
#Sta/Elev= 30
  4403.5 2119.19  4433.9 2116.93  4494.3 2113.01  4502.4 2110.61  4538.6 2108.82
  4632.9 2106.83  4693.9 2097.88  4709.0 2097.83  4800.0 2091.62  4852.6 2088.77
  4897.7 2079.82  4911.3 2083.41  4921.6 2083.14  4947.8 2079.07  5001.3 2078.07
  5001.5 2077.57  5005.3 2078.07  5023.7 2078.46  5033.9 2081.97  5043.1 2087.64
  5048.2 2087.72  5054.3 2093.33  5064.5 2097.94  5074.7 2099.36  5166.7 2102.25
  5238.8 2108.78  5275.3 2108.80  5332.9 2104.82  5499.8 2105.60  5544.9 2106.88
#Mann=6,-1,0
  4403.5    0.12       0  4433.9    0.05       0  4538.6    0.12       0
  4800.0    0.05       0  5001.3    0.05       0  5005.3    0.05       0
Bank Sta=5001.3,5005.3
Exp/Cntr=0.3,0.1

Type RM Length L Ch R = 1,19064,45,45,45
BEGIN DESCRIPTION:
Elm 01 74 19063.94
END DESCRIPTION:
XS GIS Cut Line= 3
      1588519.91      6776453.64      1588354.95      6776516.15
      1588229.53      6776575.84
#Sta/Elev= 30
  4824.5 2091.58  4861.8 2088.32  4893.9 2087.16  4903.3 2085.94  4915.3 2081.34
  4919.3 2081.03  4926.0 2080.52  4933.5 2078.84  4938.8 2073.74  4947.4 2072.18
  4956.1 2071.67  4956.3 2071.17  4960.1 2071.67  4963.6 2072.51  4969.0 2071.89
  4988.4 2075.19  4993.8 2074.28  4998.2 2077.03  5003.6 2077.03  5011.6 2081.90
  5017.1 2086.12  5023.0 2088.32  5039.9 2092.63  5062.6 2093.16  5068.1 2094.25
  5078.4 2094.08  5100.5 2097.99  5130.7 2097.81  5136.2 2098.49  5139.8 2097.70
#Mann=4,-1,0
  4824.5    0.12       0  4919.3    0.05       0  4956.1    0.05       0
  4960.1    0.05       0
Bank Sta=4956.1,4960.1
Exp/Cntr=0.3,0.1

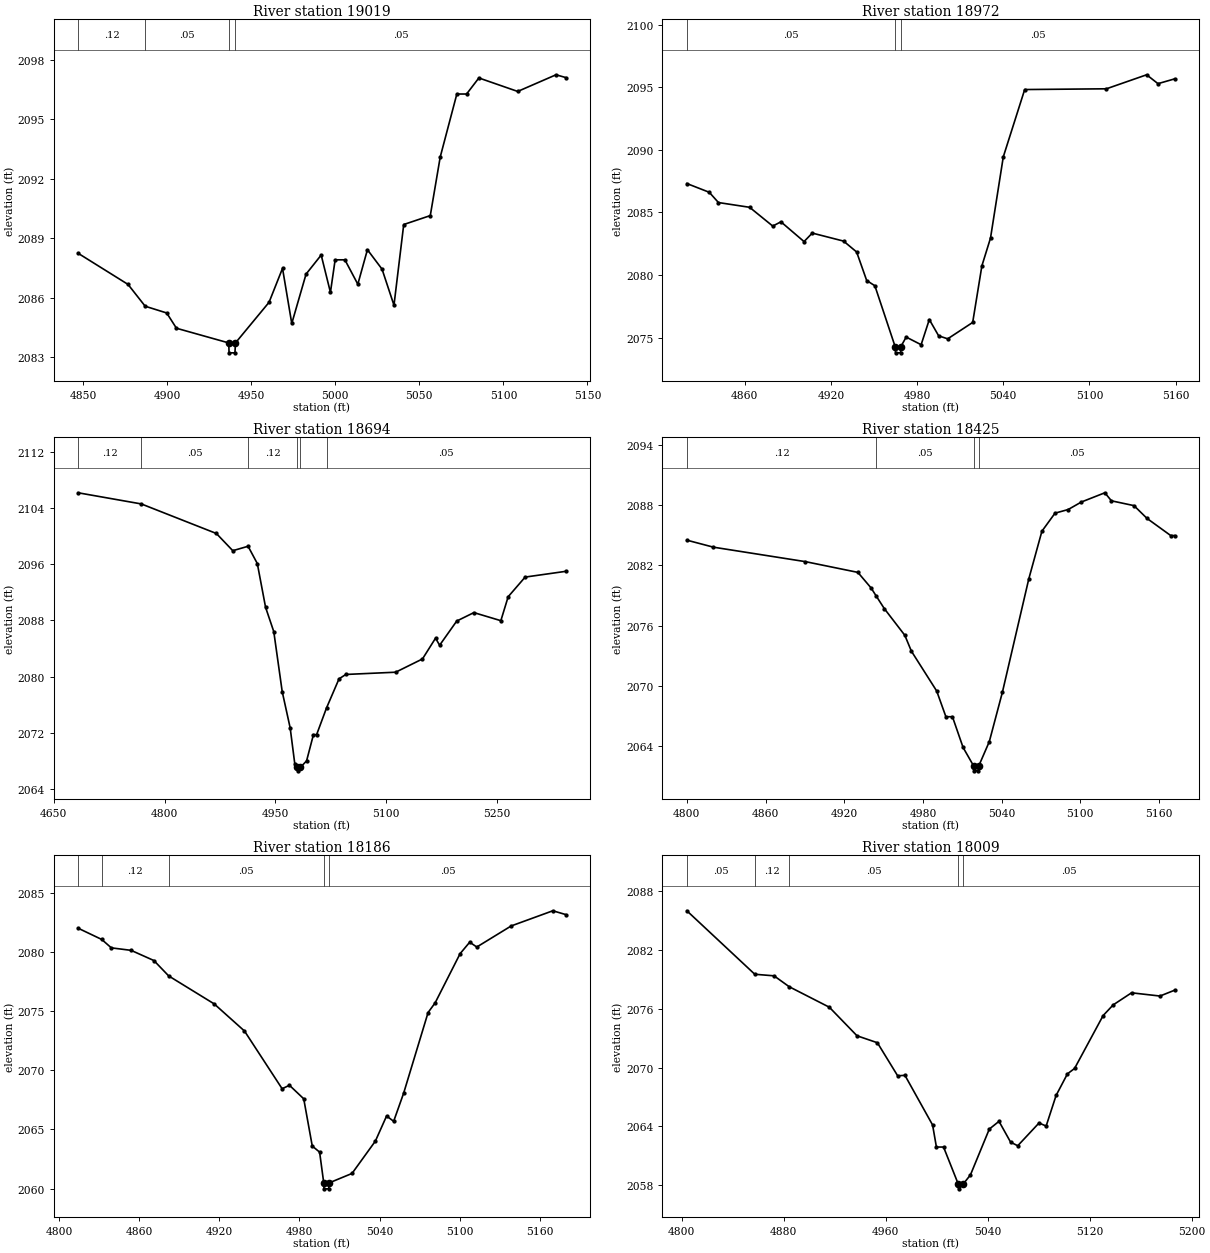
Type RM Length L Ch R = 1,19019,47,47,47
BEGIN DESCRIPTION:
Elm 01 74 19018.74
END DESCRIPTION:
XS GIS Cut Line= 3
      1588478.19      6776411.13      1588338.46      6776475.35
      1588220.15      6776543.08
#Sta/Elev= 30
  4847.0 2088.24  4876.7 2086.67  4886.9 2085.57  4899.7 2085.23  4905.5 2084.46
  4936.6 2083.72  4936.8 2083.22  4940.3 2083.22  4940.6 2083.72  4960.6 2085.77
  4968.6 2087.48  4974.1 2084.70  4982.6 2087.19  4991.6 2088.15  4997.1 2086.27
  4999.9 2087.91  5005.7 2087.91  5013.4 2086.68  5019.1 2088.42  5027.8 2087.44
  5034.9 2085.62  5040.7 2089.69  5056.5 2090.14  5062.4 2093.09  5072.3 2096.27
  5078.1 2096.27  5085.4 2097.08  5108.5 2096.40  5131.3 2097.24  5137.1 2097.10
#Mann=4,-1,0
  4847.0    0.12       0  4886.9    0.05       0  4936.6    0.05       0
  4940.6    0.05       0
Bank Sta=4936.6,4940.6
Exp/Cntr=0.3,0.1

Type RM Length L Ch R = 1,18972,278,278,278
BEGIN DESCRIPTION:
Elm 01 74 18972.49
END DESCRIPTION:
XS GIS Cut Line= 3
      1588468.64      6776352.11      1588308.94      6776439.76
      1588178.97      6776528.42
#Sta/Elev= 30
  4819.7 2087.31  4835.3 2086.61  4841.7 2085.79  4863.4 2085.41  4879.5 2083.91
  4885.2 2084.25  4901.3 2082.67  4907.0 2083.35  4928.8 2082.71  4937.9 2081.84
  4944.9 2079.56  4950.6 2079.14  4964.7 2074.28  4965.0 2073.78  4968.5 2073.78
  4968.7 2074.28  4972.4 2075.04  4982.8 2074.43  4988.5 2076.44  4995.0 2075.14
  5001.3 2074.90  5018.7 2076.21  5025.1 2080.73  5031.1 2082.95  5040.0 2089.44
  5054.9 2094.82  5111.8 2094.88  5139.8 2096.00  5147.7 2095.29  5159.2 2095.67
#Mann=3,-1,0
  4819.7    0.05       0  4964.7    0.05       0  4968.7    0.05       0
Bank Sta=4964.7,4968.7
Exp/Cntr=0.3,0.1

Type RM Length L Ch R = 1,18694,269,269,269
BEGIN DESCRIPTION:
Elm 01 74 18694.38
END DESCRIPTION:
XS GIS Cut Line= 3
      1588447.71      6775909.39      1588308.83      6776197.57
      1588169.98      6776508.25
#Sta/Elev= 30
  4683.0 2106.18  4768.6 2104.59  4870.2 2100.38  4892.4 2097.93  4913.1 2098.56
  4925.6 2096.10  4936.8 2089.86  4947.9 2086.40  4959.3 2077.86  4970.1 2072.68
  4976.4 2067.51  4980.0 2067.07  4980.2 2066.57  4984.0 2067.07  4992.3 2067.99
  5001.6 2071.73  5005.9 2071.73  5019.3 2075.53  5036.2 2079.67  5045.4 2080.30
  5112.9 2080.62  5149.2 2082.51  5166.9 2085.47  5172.4 2084.46  5195.6 2087.91
  5218.8 2089.11  5255.3 2087.96  5265.2 2091.37  5288.2 2094.17  5343.2 2094.99
#Mann=6,-1,0
  4683.0    0.12       0  4768.6    0.05       0  4913.1    0.12       0
  4980.0    0.07       0  4984.0    0.12       0  5019.3    0.05       0
Bank Sta=4980,4984
Exp/Cntr=0.3,0.1

Type RM Length L Ch R = 1,18425,239,239,239
BEGIN DESCRIPTION:
Elm 01 74 18424.53
END DESCRIPTION:
XS GIS Cut Line= 3
      1588088.72      6776087.74      1588078.30      6776286.98
      1588066.58      6776458.87
#Sta/Elev= 30
  4800.0 2084.51  4820.3 2083.81  4890.4 2082.37  4930.4 2081.30  4940.4 2079.76
  4944.5 2078.92  4950.5 2077.70  4966.2 2075.03  4971.2 2073.45  4990.5 2069.48
  4997.5 2066.92  5002.5 2066.92  5010.6 2063.86  5018.6 2062.03  5018.8 2061.53
  5022.3 2061.53  5022.6 2062.03  5030.6 2064.44  5040.6 2069.37  5060.7 2080.65
  5070.7 2085.40  5080.7 2087.20  5090.7 2087.56  5100.8 2088.31  5118.7 2089.23
  5123.7 2088.43  5140.9 2087.95  5150.9 2086.67  5168.9 2084.97  5171.8 2084.97
#Mann=4,-1,0
  4800.0    0.12       0  4944.5    0.05       0  5018.6    0.05       0
  5022.6    0.05       0
Bank Sta=5018.6,5022.6
Exp/Cntr=0.3,0.1

Type RM Length L Ch R = 1,18186,177,177,177
BEGIN DESCRIPTION:
Elm 01 74 18186.22
END DESCRIPTION:
XS GIS Cut Line= 3
      1587936.39      6776065.60      1587855.65      6776233.60
      1587797.06      6776402.85
#Sta/Elev= 30
  4814.1 2081.99  4831.8 2081.04  4839.0 2080.33  4853.8 2080.12  4870.9 2079.26
  4882.0 2077.96  4916.1 2075.60  4938.8 2073.31  4967.0 2068.44  4972.5 2068.73
  4983.2 2067.59  4989.6 2063.60  4995.1 2063.09  4998.2 2060.49  4998.4 2059.99
  5001.9 2059.99  5002.2 2060.49  5019.4 2061.29  5036.9 2064.02  5045.3 2066.14
  5050.6 2065.69  5058.1 2068.07  5076.4 2074.87  5081.7 2075.69  5100.4 2079.84
  5107.6 2080.81  5112.9 2080.40  5138.7 2082.18  5169.9 2083.46  5179.6 2083.14
#Mann=5,-1,0
  4814.1    0.05       0  4831.8    0.12       0  4882.0    0.05       0
  4998.2    0.05       0  5002.2    0.05       0
Bank Sta=4998.2,5002.2
Exp/Cntr=0.3,0.1

Type RM Length L Ch R = 1,18009,164,164,164
BEGIN DESCRIPTION:
Elm 01 74 18009.3
END DESCRIPTION:
XS GIS Cut Line= 3
      1587803.48      6775973.34      1587707.12      6776145.23
      1587623.80      6776311.01
#Sta/Elev= 30
  4803.9 2085.98  4857.2 2079.51  4872.3 2079.35  4884.2 2078.24  4915.7 2076.15
  4937.4 2073.24  4953.4 2072.53  4969.3 2069.16  4975.0 2069.21  4996.7 2064.15
  4999.7 2061.90  5005.3 2061.90  5016.8 2058.14  5017.1 2057.64  5020.8 2058.14
  5026.4 2059.06  5041.2 2063.73  5048.8 2064.52  5057.9 2062.40  5063.5 2062.03
  5080.2 2064.35  5085.8 2064.04  5093.6 2067.16  5102.5 2069.36  5108.1 2069.91
  5130.5 2075.30  5138.4 2076.39  5152.8 2077.62  5175.1 2077.29  5186.5 2077.88
#Mann=5,-1,0
  4803.9    0.05       0  4857.2    0.12       0  4884.2    0.05       0
  5016.8    0.05       0  5020.8    0.05       0
Bank Sta=5016.8,5020.8
Exp/Cntr=0.3,0.1

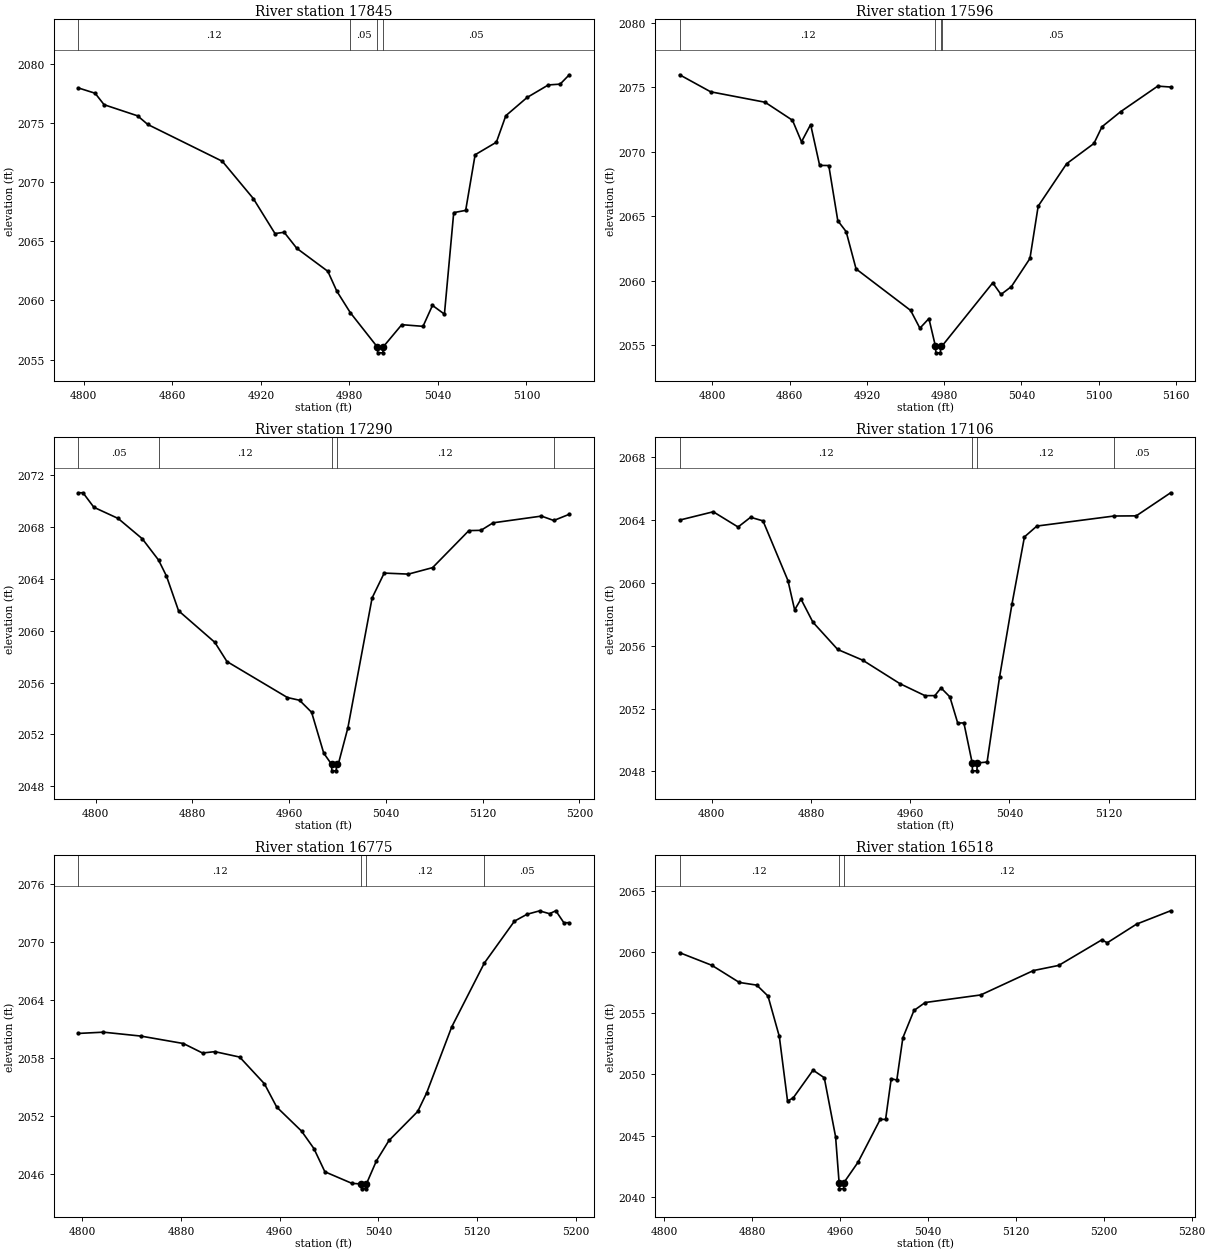
Type RM Length L Ch R = 1,17845,249,249,249
BEGIN DESCRIPTION:
Elm 01 74 17845.08
END DESCRIPTION:
XS GIS Cut Line= 3
      1587677.63      6775915.16      1587559.55      6776082.73
      1587479.98      6776182.62
#Sta/Elev= 30
  4796.3 2077.96  4807.7 2077.51  4813.8 2076.54  4836.5 2075.60  4843.4 2074.87
  4893.9 2071.76  4914.9 2068.61  4929.6 2065.65  4935.8 2065.76  4944.4 2064.40
  4965.4 2062.46  4971.5 2060.78  4980.6 2058.97  4998.9 2056.07  4999.2 2055.57
  5002.7 2055.57  5002.9 2056.07  5015.5 2057.95  5029.9 2057.81  5036.3 2059.58
  5044.4 2058.84  5050.7 2067.42  5058.8 2067.61  5065.2 2072.31  5079.6 2073.37
  5086.0 2075.61  5100.4 2077.15  5114.8 2078.21  5122.8 2078.28  5129.0 2079.07
#Mann=4,-1,0
  4796.3    0.12       0  4980.6    0.05       0  4998.9    0.05       0
  5002.9    0.05       0
Bank Sta=4998.9,5002.9
Exp/Cntr=0.3,0.1

Type RM Length L Ch R = 1,17596,306,306,306
BEGIN DESCRIPTION:
Elm 01 74 17596.08
END DESCRIPTION:
XS GIS Cut Line= 3
      1587572.41      6775731.46      1587409.68      6775890.93
      1587314.23      6776011.34
#Sta/Elev= 30
  4774.5 2075.97  4798.6 2074.65  4840.9 2073.84  4862.2 2072.44  4869.2 2070.77
  4876.3 2072.11  4883.3 2068.94  4890.4 2068.93  4897.4 2064.65  4903.9 2063.80
  4911.6 2060.91  4954.0 2057.69  4961.2 2056.31  4968.2 2057.06  4973.3 2054.90
  4973.6 2054.40  4977.1 2054.40  4977.4 2054.90  4978.4 2054.93  5017.8 2059.83
  5024.2 2058.93  5032.3 2059.54  5046.7 2061.72  5053.1 2065.78  5075.2 2069.07
  5096.4 2070.64  5102.7 2071.94  5117.2 2073.11  5146.0 2075.09  5156.0 2075.02
#Mann=4,-1,0
  4774.5    0.12       0  4973.3    0.05       0  4977.4    0.12       0
  4978.4    0.05       0
Bank Sta=4973.3,4977.4
Exp/Cntr=0.3,0.1

Type RM Length L Ch R = 1,17290,184,184,184
BEGIN DESCRIPTION:
Elm 01 74 17289.82
END DESCRIPTION:
XS GIS Cut Line= 3
      1587190.50      6775575.14      1587194.84      6775790.02
      1587195.92      6775980.99
#Sta/Elev= 30
  4785.7 2070.65  4789.6 2070.65  4798.6 2069.53  4818.6 2068.67  4838.6 2067.10
  4852.1 2065.45  4858.6 2064.22  4868.6 2061.54  4898.6 2059.10  4908.6 2057.62
  4958.6 2054.84  4968.6 2054.63  4978.6 2053.70  4988.6 2050.55  4995.1 2049.68
  4995.3 2049.18  4998.9 2049.18  4999.2 2049.68  5000.6 2049.68  5008.6 2052.51
  5028.6 2062.53  5038.6 2064.45  5058.6 2064.37  5078.6 2064.87  5108.6 2067.73
  5118.6 2067.75  5128.6 2068.33  5168.6 2068.85  5178.8 2068.51  5191.6 2068.99
#Mann=5,-1,0
  4785.7    0.05       0  4852.1    0.12       0  4995.1    0.07       0
  4999.2    0.12       0  5178.8    0.05       0
Bank Sta=4995.1,4999.2
Exp/Cntr=0.3,0.1

Type RM Length L Ch R = 1,17106,331,331,331
BEGIN DESCRIPTION:
Elm 01 74 17106.34
END DESCRIPTION:
XS GIS Cut Line= 3
      1586991.93      6775561.05      1587011.46      6775785.68
      1587020.07      6775955.68
#Sta/Elev= 30
  4774.2 2064.01  4801.3 2064.54  4821.3 2063.57  4831.4 2064.19  4841.4 2063.96
  4861.5 2060.16  4866.9 2058.29  4872.0 2058.98  4881.6 2057.51  4901.6 2055.77
  4921.7 2055.09  4951.8 2053.59  4971.9 2052.83  4979.9 2052.83  4984.9 2053.32
  4992.0 2052.75  4998.3 2051.09  5003.3 2051.09  5010.0 2048.54  5010.2 2048.04
  5013.8 2048.04  5014.1 2048.54  5022.0 2048.60  5032.0 2053.99  5042.1 2058.68
  5052.1 2062.94  5062.1 2063.63  5124.3 2064.27  5142.2 2064.28  5169.9 2065.75
#Mann=4,-1,0
  4774.2    0.12       0  5010.0    0.07       0  5014.1    0.12       0
  5124.3    0.05       0
Bank Sta=5010,5014.1
Exp/Cntr=0.3,0.1

Type RM Length L Ch R = 1,16775,257,257,257
BEGIN DESCRIPTION:
Elm 01 74 16775.22
END DESCRIPTION:
XS GIS Cut Line= 3
      1586765.41      6775577.61      1586752.39      6775780.72
      1586717.67      6775971.67
#Sta/Elev= 30
  4796.9 2060.53  4817.3 2060.66  4847.4 2060.26  4882.0 2059.49  4897.5 2058.51
  4907.5 2058.65  4927.6 2058.09  4947.6 2055.34  4957.6 2052.93  4977.7 2050.45
  4987.7 2048.65  4996.6 2046.25  5018.4 2045.06  5026.0 2044.99  5026.3 2044.49
  5030.0 2044.49  5030.2 2044.99  5038.3 2047.37  5048.5 2049.48  5071.8 2052.48
  5079.0 2054.39  5099.3 2061.20  5125.7 2067.79  5150.1 2072.12  5160.3 2072.83
  5170.4 2073.18  5178.5 2072.89  5183.6 2073.19  5190.1 2071.96  5194.5 2071.96
#Mann=4,-1,0
  4796.9    0.12       0  5026.0    0.07       0  5030.2    0.12       0
  5125.7    0.05       0
Bank Sta=5026,5030.2
Exp/Cntr=0.3,0.1

Type RM Length L Ch R = 1,16518,339,339,339
BEGIN DESCRIPTION:
Elm 01 74 16518.26
END DESCRIPTION:
XS GIS Cut Line= 3
      1586591.44      6775449.40      1586551.52      6775632.51
      1586510.73      6775888.57
#Sta/Elev= 30
  4814.1 2059.94  4843.4 2058.91  4868.4 2057.51  4884.3 2057.29  4894.5 2056.40
  4904.8 2053.10  4912.3 2047.82  4917.5 2048.09  4935.5 2050.35  4945.7 2049.73
  4956.0 2044.91  4959.2 2041.16  4959.5 2040.66  4963.2 2040.66  4963.5 2041.16
  4976.4 2042.83  4996.6 2046.33  5001.5 2046.33  5006.6 2049.65  5011.7 2049.54
  5017.2 2052.99  5027.3 2055.22  5037.5 2055.87  5088.1 2056.49  5136.0 2058.48
  5159.0 2058.90  5198.1 2060.98  5203.2 2060.75  5229.8 2062.27  5260.8 2063.36
#Mann=3,-1,0
  4814.1    0.12       0  4959.2    0.07       0  4963.5    0.12       0
Bank Sta=4959.2,4963.5
Exp/Cntr=0.3,0.1

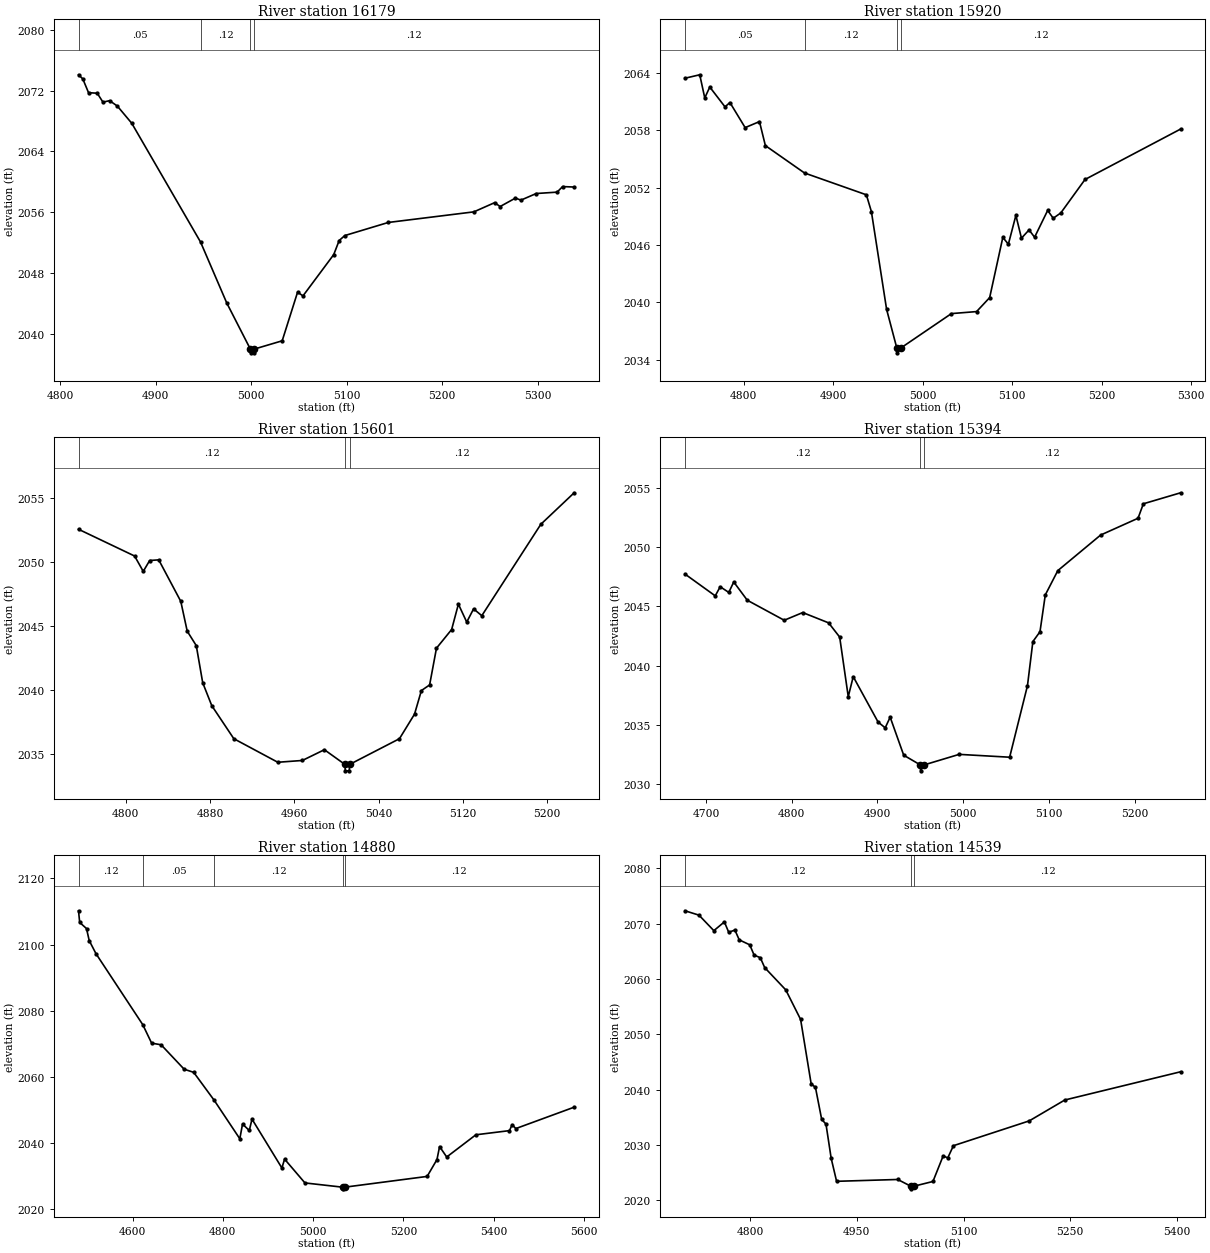
Type RM Length L Ch R = 1,16179,259,259,259
BEGIN DESCRIPTION:
Elm 01 74 16179.48
END DESCRIPTION:
XS GIS Cut Line= 3
      1586156.58      6775440.71      1586256.38      6775593.45
      1586418.71      6775888.60
#Sta/Elev= 30
  4819.1 2074.07  4823.6 2073.53  4829.6 2071.72  4838.7 2071.65  4844.7 2070.48
  4851.7 2070.67  4859.8 2069.96  4874.9 2067.70  4947.0 2052.10  4974.4 2044.11
  4999.1 2038.06  4999.4 2037.56  5003.2 2037.56  5003.4 2038.06  5032.5 2039.14
  5048.6 2045.52  5054.3 2045.04  5086.5 2050.46  5092.2 2052.31  5098.1 2052.96
  5143.7 2054.68  5233.3 2056.07  5255.1 2057.28  5260.8 2056.77  5276.9 2057.88
  5282.6 2057.61  5298.7 2058.48  5320.5 2058.66  5326.3 2059.39  5338.4 2059.33
#Mann=4,-1,0
  4819.1    0.05       0  4947.0    0.12       0  4999.1    0.07       0
  5003.4    0.12       0
Bank Sta=4999.1,5003.4
Exp/Cntr=0.3,0.1

Type RM Length L Ch R = 1,15920,319,319,319
BEGIN DESCRIPTION:
Elm 01 74 15920.27
END DESCRIPTION:
XS GIS Cut Line= 3
      1585860.19      6775673.31      1586099.79      6775789.63
      1586331.24      6775959.77
#Sta/Elev= 30
  4734.5 2063.43  4751.0 2063.79  4756.6 2061.37  4762.2 2062.51  4779.2 2060.44
  4784.7 2060.89  4801.7 2058.27  4817.7 2058.90  4824.3 2056.39  4868.0 2053.53
  4937.1 2051.25  4942.7 2049.50  4959.7 2039.28  4971.1 2035.24  4971.4 2034.74
  4975.5 2035.24  5032.1 2038.84  5060.2 2039.05  5074.8 2040.51  5089.5 2046.80
  5095.7 2046.09  5104.1 2049.10  5110.3 2046.72  5118.8 2047.58  5125.0 2046.82
  5139.6 2049.62  5145.8 2048.80  5154.3 2049.36  5181.3 2052.85  5288.1 2058.12
#Mann=4,-1,0
  4734.5    0.05       0  4868.0    0.12       0  4971.1    0.07       0
  4975.5    0.12       0
Bank Sta=4971.1,4975.5
Exp/Cntr=0.3,0.1

Type RM Length L Ch R = 1,15601,207,207,207
BEGIN DESCRIPTION:
Elm 01 74 15601.48
END DESCRIPTION:
XS GIS Cut Line= 3
      1585762.97      6775794.82      1585906.21      6775993.63
      1586079.82      6776136.85
#Sta/Elev= 30
  4755.4 2052.52  4808.6 2050.43  4816.8 2049.23  4822.9 2050.08  4831.5 2050.13
  4852.4 2046.89  4858.5 2044.56  4867.1 2043.43  4873.2 2040.53  4881.8 2038.74
  4902.7 2036.16  4944.4 2034.32  4967.7 2034.46  4988.6 2035.30  5008.1 2034.15
  5008.4 2033.65  5012.2 2033.65  5012.5 2034.15  5059.8 2036.16  5074.1 2038.08
  5080.6 2039.92  5088.4 2040.36  5094.9 2043.23  5109.3 2044.69  5115.7 2046.67
  5123.6 2045.27  5130.1 2046.30  5137.9 2045.77  5193.9 2052.91  5225.5 2055.37
#Mann=3,-1,0
  4755.4    0.12       0  5008.1    0.07       0  5012.5    0.12       0
Bank Sta=5008.1,5012.5
Exp/Cntr=0.3,0.1

Type RM Length L Ch R = 1,15394,514,514,514
BEGIN DESCRIPTION:
Elm 01 74 15393.68
END DESCRIPTION:
XS GIS Cut Line= 3
      1585592.21      6775852.70      1585754.56      6776134.86
      1585907.33      6776336.23
#Sta/Elev= 30
  4675.4 2047.72  4710.7 2045.88  4716.5 2046.65  4726.5 2046.17  4732.3 2047.05
  4748.1 2045.51  4791.2 2043.82  4812.8 2044.47  4843.0 2043.60  4855.9 2042.40
  4865.9 2037.37  4871.7 2039.06  4900.7 2035.23  4909.0 2034.74  4914.8 2035.64
  4930.6 2032.43  4950.0 2031.61  4950.3 2031.11  4954.4 2031.61  4995.3 2032.50
  5054.2 2032.26  5075.0 2038.30  5081.3 2042.02  5089.6 2042.85  5095.8 2045.96
  5110.4 2048.01  5160.3 2051.01  5204.0 2052.43  5210.2 2053.65  5253.7 2054.58
#Mann=3,-1,0
  4675.4    0.12       0  4950.0    0.07       0  4954.4    0.12       0
Bank Sta=4950,4954.4
Exp/Cntr=0.3,0.1

Type RM Length L Ch R = 1,14880,341,341,341
BEGIN DESCRIPTION:
Elm 01 74 14880.16
END DESCRIPTION:
XS GIS Cut Line= 3
      1584969.45      6775659.43      1585258.49      6776094.30
      1585756.86      6776383.17
#Sta/Elev= 30
  4480.2 2110.22  4482.8 2106.69  4497.9 2104.84  4503.9 2101.20  4518.9 2097.23
  4622.6 2075.72  4642.2 2070.13  4663.2 2069.64  4714.3 2062.23  4735.4 2061.29
  4781.0 2052.79  4837.6 2041.17  4843.6 2045.63  4858.6 2043.68  4864.6 2047.12
  4930.8 2032.33  4936.8 2035.01  4981.9 2027.80  5065.4 2026.51  5065.7 2026.01
  5069.9 2026.51  5252.6 2029.77  5274.4 2034.87  5280.2 2038.81  5296.0 2035.65
  5360.6 2042.38  5435.1 2043.64  5440.9 2045.45  5449.1 2044.26  5578.4 2050.74
#Mann=5,-1,0
  4480.2    0.12       0  4622.6    0.05       0  4781.0    0.12       0
  5065.4    0.07       0  5069.9    0.12       0
Bank Sta=5065.4,5069.9
Exp/Cntr=0.3,0.1

Type RM Length L Ch R = 1,14539,338,338,338
BEGIN DESCRIPTION:
Elm 01 74 14539.03
END DESCRIPTION:
XS GIS Cut Line= 3
      1584726.69      6776059.76      1584966.30      6776227.83
      1585280.46      6776482.35
#Sta/Elev= 30
  4708.3 2072.30  4728.0 2071.51  4748.9 2068.71  4763.7 2070.29  4769.8 2068.42
  4778.5 2068.82  4784.6 2067.05  4799.4 2066.15  4805.5 2064.30  4814.2 2063.83
  4820.4 2062.04  4850.0 2058.02  4870.9 2052.68  4885.7 2041.08  4891.8 2040.39
  4900.5 2034.65  4906.6 2033.77  4913.9 2027.60  4921.5 2023.45  5007.5 2023.78
  5025.5 2022.59  5026.0 2022.09  5031.0 2022.59  5057.0 2023.42  5071.4 2028.05
  5077.8 2027.67  5085.8 2029.88  5192.4 2034.36  5242.4 2038.13  5405.3 2043.23
#Mann=3,-1,0
  4708.3    0.12       0  5025.5    0.07       0  5031.0    0.12       0
Bank Sta=5025.5,5031
Exp/Cntr=0.3,0.1

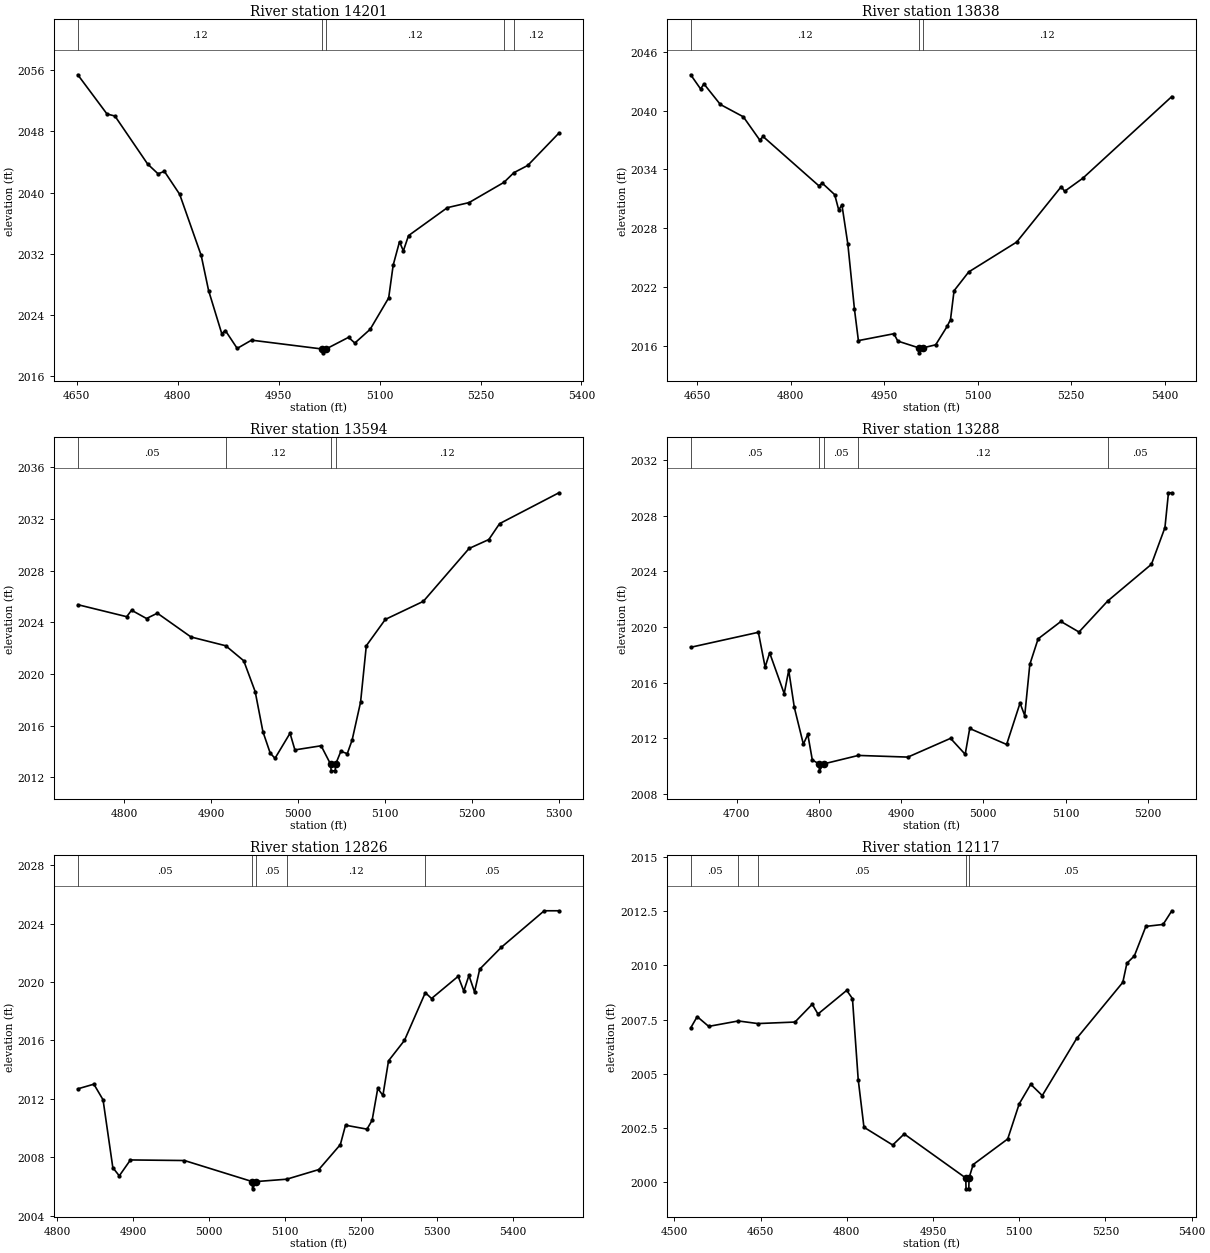
Type RM Length L Ch R = 1,14201,363,363,363
BEGIN DESCRIPTION:
Elm 01 74 14200.83
END DESCRIPTION:
XS GIS Cut Line= 3
      1584633.19      6776156.37      1584756.87      6776484.46
      1584932.17      6776803.89
#Sta/Elev= 30
  4651.5 2055.42  4694.9 2050.29  4706.7 2050.02  4755.3 2043.74  4770.8 2042.46
  4780.2 2042.78  4802.9 2039.78  4834.9 2031.77  4845.9 2027.18  4865.4 2021.56
  4870.8 2021.95  4888.4 2019.61  4909.7 2020.69  5014.8 2019.53  5015.3 2019.03
  5020.3 2019.53  5053.9 2021.06  5063.2 2020.31  5086.0 2022.11  5113.5 2026.22
  5120.2 2030.51  5129.6 2033.57  5135.3 2032.37  5143.0 2034.37  5200.7 2038.03
  5232.9 2038.69  5284.8 2041.34  5299.6 2042.61  5320.1 2043.55  5366.5 2047.79
#Mann=5,-1,0
  4651.5    0.12       0  5014.8    0.07       0  5020.3    0.12       0
  5284.8    0.05       0  5299.6    0.12       0
Bank Sta=5014.8,5020.3
Exp/Cntr=0.3,0.1

Type RM Length L Ch R = 1,13838,244,244,244
BEGIN DESCRIPTION:
Elm 01 74 13838.18
END DESCRIPTION:
XS GIS Cut Line= 3
      1584294.64      6776188.91      1584409.21      6776532.64
      1584566.77      6776910.26
#Sta/Elev= 30
  4639.7 2043.65  4655.6 2042.20  4660.9 2042.72  4687.2 2040.62  4724.1 2039.36
  4750.5 2036.98  4755.7 2037.35  4845.3 2032.31  4850.6 2032.59  4870.6 2031.41
  4877.0 2029.86  4882.2 2030.36  4891.7 2026.35  4902.3 2019.70  4908.6 2016.51
  4965.5 2017.21  4971.8 2016.46  5005.9 2015.76  5006.3 2015.26  5011.5 2015.76
  5032.5 2016.08  5050.9 2017.96  5056.3 2018.66  5062.0 2021.60  5085.5 2023.52
  5162.4 2026.57  5233.9 2032.23  5239.3 2031.75  5268.5 2033.09  5411.2 2041.43
#Mann=3,-1,0
  4639.7    0.12       0  5005.9    0.07       0  5011.5    0.12       0
Bank Sta=5005.9,5011.5
Exp/Cntr=0.3,0.1

Type RM Length L Ch R = 1,13594,306,306,306
BEGIN DESCRIPTION:
Elm 01 74 13593.86
END DESCRIPTION:
XS GIS Cut Line= 3
      1584094.59      6776415.12      1584202.25      6776644.32
      1584344.60      6776909.05
#Sta/Elev= 30
  4746.5 2025.37  4802.8 2024.44  4808.4 2024.94  4825.6 2024.30  4838.1 2024.71
  4876.8 2022.87  4916.8 2022.19  4937.5 2021.03  4950.7 2018.64  4959.6 2015.54
  4968.0 2013.88  4973.5 2013.48  4990.8 2015.42  4996.4 2014.13  5026.6 2014.45
  5037.6 2013.01  5038.1 2012.51  5042.8 2012.51  5043.2 2013.01  5049.3 2014.02
  5056.7 2013.84  5062.3 2014.90  5072.0 2017.83  5078.6 2022.19  5100.5 2024.23
  5144.3 2025.63  5196.9 2029.72  5219.6 2030.41  5232.0 2031.64  5300.3 2034.03
#Mann=4,-1,0
  4746.5    0.05       0  4916.8    0.12       0  5037.6    0.07       0
  5043.2    0.12       0
Bank Sta=5037.6,5043.2
Exp/Cntr=0.3,0.1

Type RM Length L Ch R = 1,13288,462,462,462
BEGIN DESCRIPTION:
Elm 01 74 13287.73
END DESCRIPTION:
XS GIS Cut Line= 3
      1583802.06      6776462.86      1583947.04      6776788.42
      1584053.82      6776990.68
#Sta/Elev= 30
  4644.1 2018.54  4726.4 2019.62  4734.6 2017.11  4740.1 2018.14  4757.8 2015.20
  4763.3 2016.88  4770.1 2014.21  4781.1 2011.56  4786.5 2012.27  4792.0 2010.42
  4800.2 2010.14  4800.6 2009.64  4805.8 2010.14  4848.0 2010.75  4908.2 2010.63
  4960.1 2011.98  4977.9 2010.83  4983.4 2012.69  5028.3 2011.54  5044.6 2014.52
  5050.3 2013.62  5056.5 2017.31  5066.6 2019.15  5094.3 2020.40  5116.3 2019.64
  5151.3 2021.88  5204.4 2024.52  5220.8 2027.16  5225.1 2029.67  5229.2 2029.67
#Mann=5,-1,0
  4644.1    0.05       0  4800.2    0.07       0  4805.8    0.05       0
  4848.0    0.12       0  5151.3    0.05       0
Bank Sta=4800.2,4805.8
Exp/Cntr=0.3,0.1

Type RM Length L Ch R = 1,12826,709,709,709
BEGIN DESCRIPTION:
Elm 01 74 12825.88
END DESCRIPTION:
XS GIS Cut Line= 4
      1583449.74      6776782.82      1583437.36      6776803.26
      1583558.01      6776890.36      1583871.11      6777229.41
#Sta/Elev= 30
  4826.8 2012.68  4848.0 2013.00  4860.1 2011.93  4873.0 2007.28  4881.5 2006.72
  4896.2 2007.81  4967.4 2007.77  5056.6 2006.33  5057.1 2005.83  5062.3 2006.33
  5102.2 2006.49  5144.5 2007.15  5172.9 2008.86  5179.7 2010.19  5208.0 2009.92
  5214.8 2010.53  5222.2 2012.71  5229.0 2012.23  5236.4 2014.60  5257.4 2016.00
  5284.9 2019.27  5293.1 2018.87  5328.2 2020.39  5335.6 2019.38  5342.4 2020.45
  5349.8 2019.32  5356.6 2020.88  5384.9 2022.37  5441.6 2024.88  5461.0 2024.88
#Mann=5,-1,0
  4826.8    0.05       0  5056.6    0.03       0  5062.3    0.05       0
  5102.2    0.12       0  5284.9    0.05       0
Bank Sta=5056.6,5062.3
Exp/Cntr=0.3,0.1

Type RM Length L Ch R = 1,12117,148,148,148
BEGIN DESCRIPTION:
Elm 01 74 12117.23
END DESCRIPTION:
XS GIS Cut Line= 3
      1583150.86      6776816.66      1583145.43      6777290.86
      1583163.87      6777653.16
#Sta/Elev= 30
  4528.4 2007.12  4539.7 2007.64  4559.7 2007.19  4611.2 2007.44  4645.2 2007.32
  4709.8 2007.39  4739.8 2008.21  4749.8 2007.76  4799.8 2008.85  4809.8 2008.47
  4819.8 2004.74  4829.8 2002.54  4879.8 2001.72  4899.8 2002.23  5006.9 2000.20
  5007.4 1999.70  5012.2 1999.70  5012.6 2000.20  5019.8 2000.82  5079.9 2002.00
  5099.9 2003.62  5119.9 2004.52  5140.0 2004.00  5200.0 2006.64  5280.1 2009.22
  5287.2 2010.10  5300.2 2010.44  5320.2 2011.80  5350.2 2011.89  5365.4 2012.52
#Mann=5,-1,0
  4528.4    0.05       0  4611.2    0.12       0  4645.2    0.05       0
  5006.9    0.05       0  5012.6    0.05       0
Bank Sta=5006.9,5012.6
Exp/Cntr=0.3,0.1