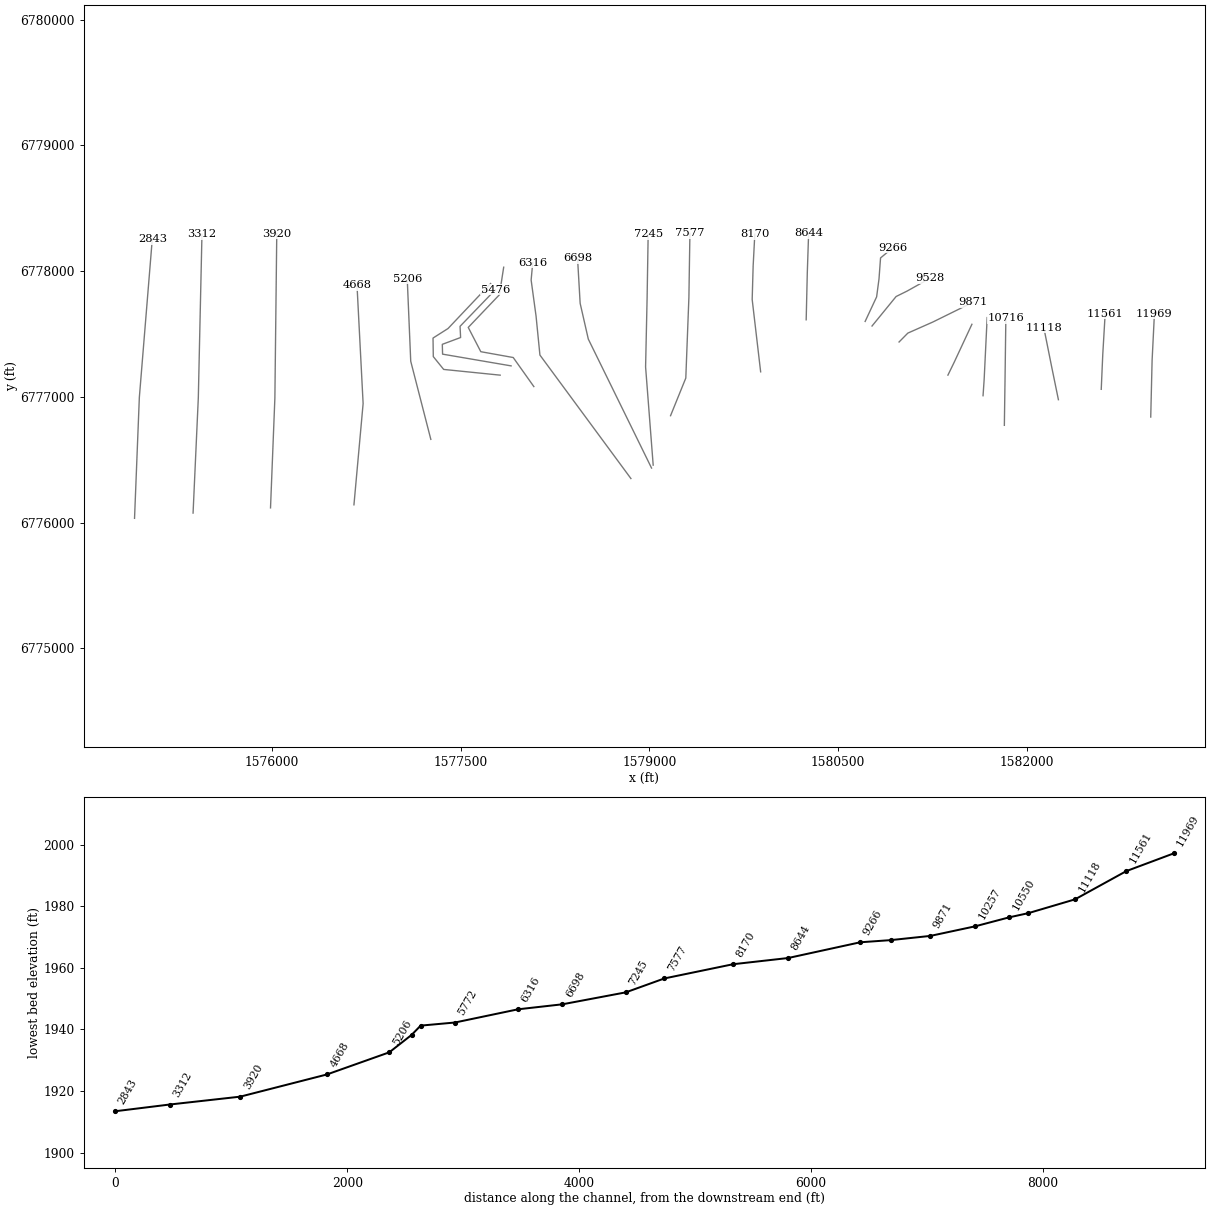
HEC-RAS study Elm 01 74.prj: Elm 01 74 Base Level Engineering

--- Elm 01 74.g01 (geometry) --- (continued)

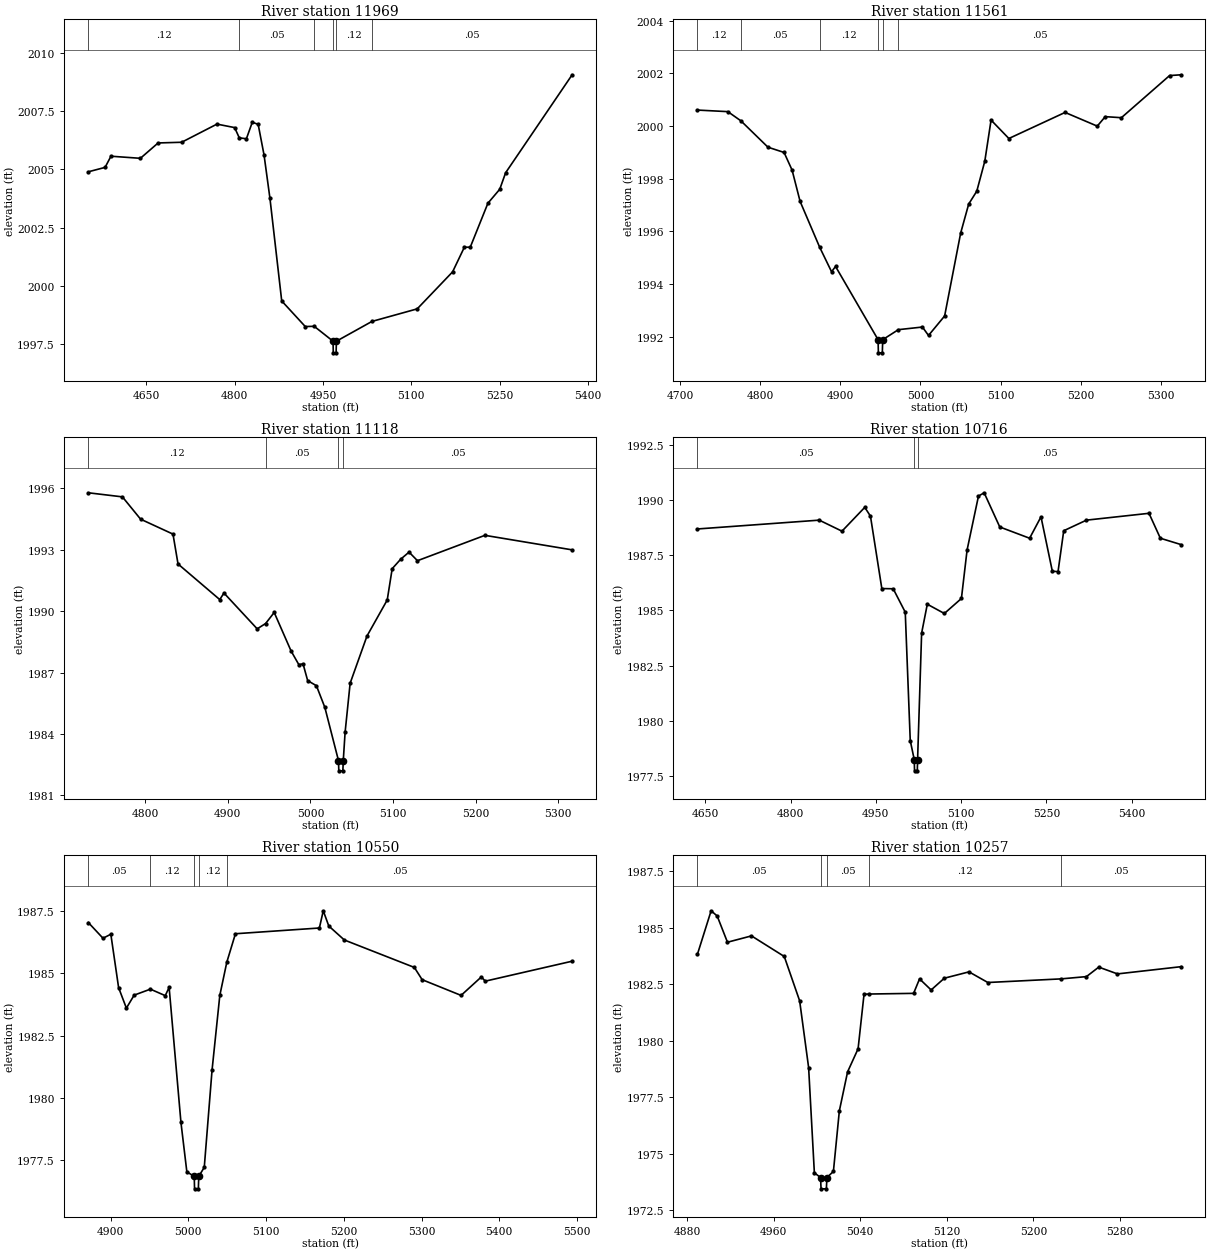
Type RM Length L Ch R = 1,11969,408,408,408
BEGIN DESCRIPTION:
Elm 01 74 11968.5
END DESCRIPTION:
XS GIS Cut Line= 3
      1582985.93      6776839.48      1582996.78      6777289.78
      1583015.23      6777660.89
#Sta/Elev= 30
  4551.3 2004.90  4579.8 2005.09  4589.8 2005.57  4639.8 2005.48  4669.9 2006.14
  4709.9 2006.17  4769.9 2006.95  4799.9 2006.80  4807.8 2006.36  4819.9 2006.32
  4829.9 2007.03  4839.9 2006.94  4849.9 2005.62  4859.9 2003.76  4879.9 1999.35
  4919.9 1998.25  4935.1 1998.26  4967.1 1997.62  4967.5 1997.12  4972.3 1997.12
  4972.8 1997.62  5033.2 1998.47  5110.1 1999.01  5170.2 2000.60  5190.2 2001.66
  5200.2 2001.66  5230.2 2003.55  5250.3 2004.15  5260.3 2004.86  5373.3 2009.07
#Mann=6,-1,0
  4551.3    0.12       0  4807.8    0.05       0  4935.1    0.12       0
  4967.1    0.07       0  4972.8    0.12       0  5033.2    0.05       0
Bank Sta=4967.1,4972.8
Exp/Cntr=0.3,0.1

Type RM Length L Ch R = 1,11561,443,443,443
BEGIN DESCRIPTION:
Elm 01 74 11560.73
END DESCRIPTION:
XS GIS Cut Line= 3
      1582592.50      6777060.04      1582604.65      6777337.81
      1582623.75      6777662.51
#Sta/Elev= 30
  4721.8 2000.60  4759.8 2000.54  4776.1 2000.19  4809.8 1999.19  4829.9 1998.99
  4839.9 1998.32  4849.9 1997.13  4874.3 1995.39  4889.1 1994.46  4894.1 1994.66
  4947.1 1991.88  4947.5 1991.38  4952.4 1991.38  4952.9 1991.88  4972.4 1992.26
  5002.4 1992.36  5010.0 1992.04  5030.1 1992.78  5050.1 1995.93  5060.1 1997.03
  5070.2 1997.52  5080.2 1998.66  5088.0 2000.22  5110.2 1999.52  5180.3 2000.51
  5220.4 1999.99  5230.4 2000.35  5250.5 2000.31  5310.6 2001.91  5325.1 2001.94
#Mann=6,-1,0
  4721.8    0.12       0  4776.1    0.05       0  4874.3    0.12       0
  4947.1    0.05       0  4952.9    0.12       0  4972.4    0.05       0
Bank Sta=4947.1,4952.9
Exp/Cntr=0.3,0.1

Type RM Length L Ch R = 1,11118,402,402,402
BEGIN DESCRIPTION:
Elm 01 74 11117.63
END DESCRIPTION:
XS GIS Cut Line= 3
      1582252.01      6776977.55      1582197.75      6777242.33
      1582135.91      6777551.52
#Sta/Elev= 30
  4731.2 1995.79  4772.5 1995.59  4794.5 1994.50  4833.7 1993.77  4839.8 1992.31
  4890.3 1990.57  4895.4 1990.89  4935.6 1989.14  4945.8 1989.40  4956.2 1989.94
  4976.6 1988.06  4986.0 1987.39  4991.1 1987.43  4996.7 1986.61  5007.3 1986.36
  5017.5 1985.30  5034.0 1982.70  5034.4 1982.20  5039.3 1982.20  5039.8 1982.70
  5042.0 1984.08  5048.1 1986.48  5068.5 1988.79  5093.0 1990.55  5099.0 1992.08
  5109.2 1992.54  5119.4 1992.89  5129.6 1992.47  5211.2 1993.71  5316.8 1993.00
#Mann=4,-1,0
  4731.2    0.12       0  4945.8    0.05       0  5034.0    0.03       0
  5039.8    0.05       0
Bank Sta=5034,5039.8
Exp/Cntr=0.3,0.1

Type RM Length L Ch R = 1,10716,166,166,166
BEGIN DESCRIPTION:
Elm 01 74 10716.42
END DESCRIPTION:
XS GIS Cut Line= 3
      1581822.32      6776773.58      1581827.74      6777139.24
      1581834.23      6777624.70
#Sta/Elev= 30
  4636.0 1988.69  4850.4 1989.09  4890.4 1988.59  4930.5 1989.67  4940.5 1989.27
  4960.5 1985.99  4980.5 1985.98  5001.7 1984.92  5010.5 1979.10  5017.6 1978.23
  5018.0 1977.73  5022.9 1977.73  5023.4 1978.23  5030.5 1983.97  5040.5 1985.28
  5070.5 1984.86  5100.5 1985.54  5110.5 1987.74  5130.5 1990.18  5140.5 1990.33
  5168.0 1988.78  5220.5 1988.27  5240.5 1989.24  5260.5 1986.77  5270.5 1986.76
  5280.5 1988.61  5320.5 1989.09  5430.5 1989.40  5450.5 1988.27  5487.2 1987.98
#Mann=3,-1,0
  4636.0    0.05       0  5017.6    0.03       0  5023.4    0.05       0
Bank Sta=5017.6,5023.4
Exp/Cntr=0.3,0.1

Type RM Length L Ch R = 1,10550,293,293,293
BEGIN DESCRIPTION:
Elm 01 74 10550.38
END DESCRIPTION:
XS GIS Cut Line= 3
      1581652.95      6777009.11      1581661.73      6777138.16
      1581685.60      6777630.73
#Sta/Elev= 30
  4871.3 1987.03  4890.2 1986.40  4900.3 1986.56  4910.3 1984.42  4920.3 1983.60
  4930.3 1984.12  4951.2 1984.36  4970.3 1984.10  4975.3 1984.43  4990.5 1979.02
  4998.1 1977.04  5007.6 1976.86  5008.0 1976.36  5012.9 1976.36  5013.4 1976.86
  5020.5 1977.22  5030.5 1981.11  5040.5 1984.11  5049.5 1985.44  5060.6 1986.58
  5168.6 1986.81  5173.6 1987.50  5180.7 1986.89  5200.7 1986.33  5290.8 1985.23
  5300.8 1984.74  5350.9 1984.11  5377.0 1984.85  5382.0 1984.68  5493.8 1985.48
#Mann=5,-1,0
  4871.3    0.05       0  4951.2    0.12       0  5007.6    0.07       0
  5013.4    0.12       0  5049.5    0.05       0
Bank Sta=5007.6,5013.4
Exp/Cntr=0.3,0.1

Type RM Length L Ch R = 1,10257,386,386,386
BEGIN DESCRIPTION:
Elm 01 74 10257.19
END DESCRIPTION:
XS GIS Cut Line= 3
      1581373.74      6777173.02      1581422.21      6777272.49
      1581564.38      6777577.43
#Sta/Elev= 30
  4889.5 1983.81  4902.2 1985.74  4907.8 1985.51  4917.3 1984.35  4939.5 1984.63
  4969.8 1983.72  4984.0 1981.76  4992.3 1978.81  4997.6 1974.16  5003.3 1973.95
  5003.8 1973.45  5008.7 1973.45  5009.2 1973.95  5015.2 1974.22  5020.7 1976.90
  5028.3 1978.62  5038.0 1979.64  5043.5 1982.05  5047.8 1982.06  5089.3 1982.09
  5094.8 1982.73  5105.5 1982.24  5117.7 1982.76  5140.5 1983.04  5157.9 1982.57
  5225.6 1982.73  5249.0 1982.83  5260.4 1983.25  5277.7 1982.95  5336.6 1983.27
#Mann=5,-1,0
  4889.5    0.05       0  5003.3    0.05       0  5009.2    0.05       0
  5047.8    0.12       0  5225.6    0.05       0
Bank Sta=5003.3,5009.2
Exp/Cntr=0.3,0.1

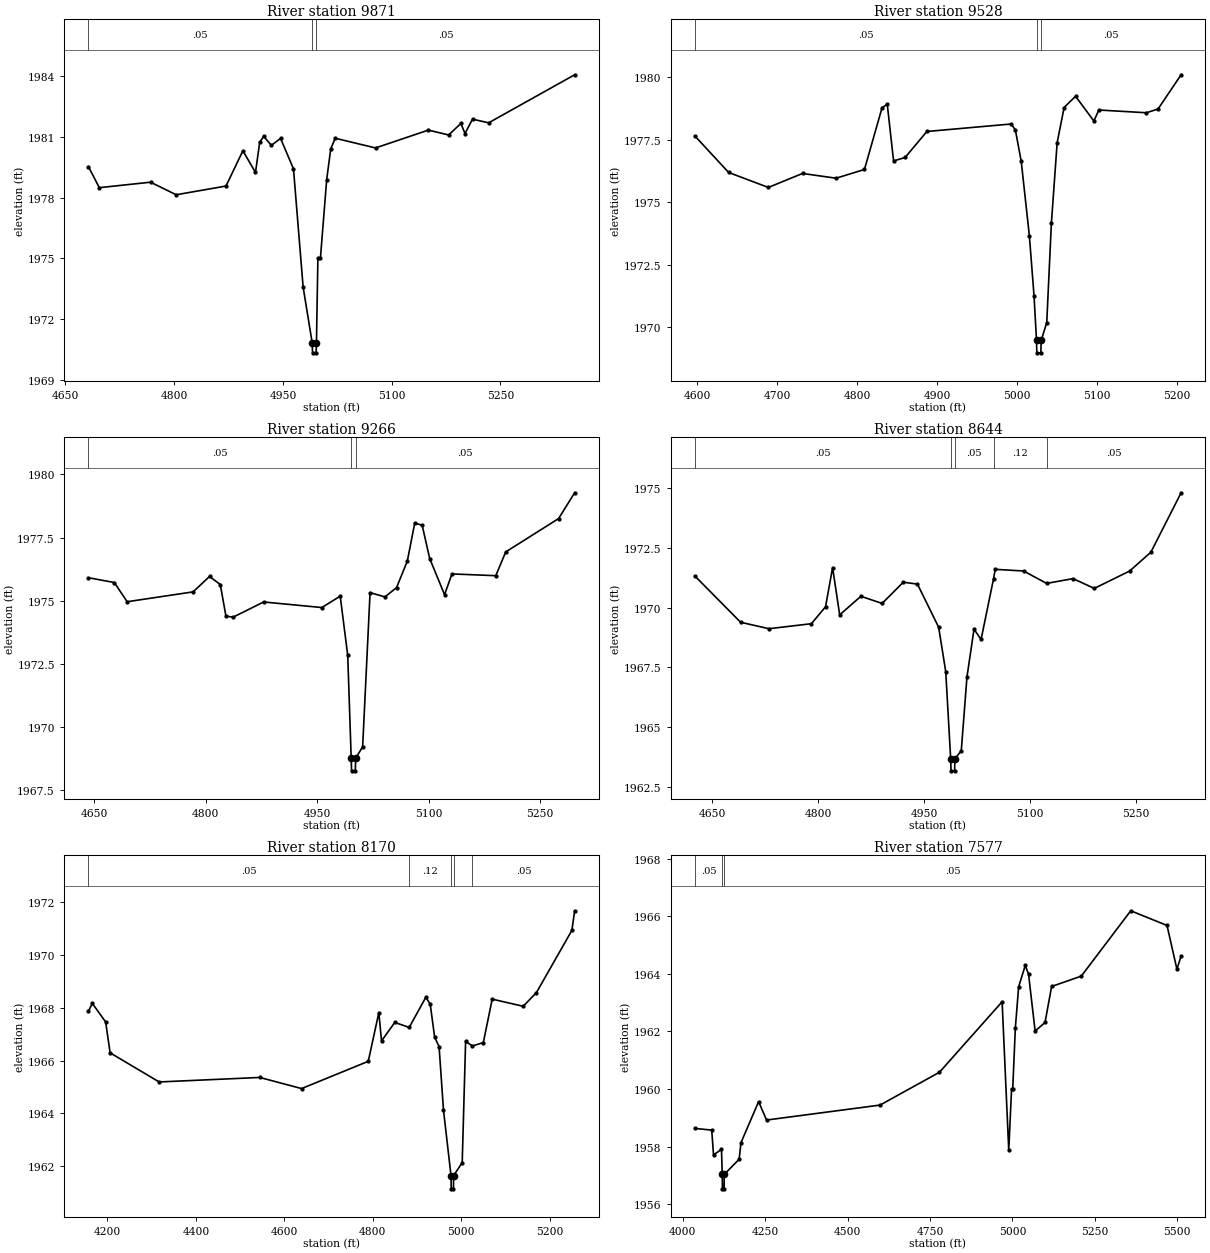
Type RM Length L Ch R = 1,9871,343,343,343
BEGIN DESCRIPTION:
Elm 01 74 9871.15
END DESCRIPTION:
XS GIS Cut Line= 4
      1580985.32      6777436.58      1581055.16      6777507.36
      1581253.67      6777595.39      1581571.34      6777752.07
#Sta/Elev= 30
  4681.7 1979.53  4696.7 1978.49  4767.4 1978.76  4802.8 1978.14  4871.5 1978.57
  4894.8 1980.31  4912.2 1979.24  4918.0 1980.73  4923.5 1981.02  4934.1 1980.58
  4946.8 1980.92  4964.6 1979.42  4977.9 1973.59  4990.4 1970.84  4990.9 1970.34
  4995.8 1970.34  4996.3 1970.84  4998.3 1975.02  5001.8 1975.02  5010.4 1978.88
  5016.0 1980.40  5022.1 1980.93  5077.8 1980.45  5150.7 1981.33  5178.7 1981.09
  5195.6 1981.66  5201.2 1981.16  5211.6 1981.87  5233.9 1981.69  5352.5 1984.06
#Mann=3,-1,0
  4681.7    0.05       0  4990.4    0.05       0  4996.3    0.05       0
Bank Sta=4990.4,4996.3
Exp/Cntr=0.3,0.1

Type RM Length L Ch R = 1,9528,262,262,262
BEGIN DESCRIPTION:
Elm 01 74 9528.24
END DESCRIPTION:
XS GIS Cut Line= 4
      1580770.49      6777563.76      1580961.79      6777798.35
      1581049.40      6777841.79      1581230.14      6777942.92
#Sta/Elev= 30
  4597.4 1977.65  4639.6 1976.19  4689.2 1975.59  4731.9 1976.15  4773.9 1975.96
  4809.3 1976.31  4831.3 1978.78  4837.8 1978.92  4845.7 1976.65  4860.1 1976.79
  4887.3 1977.83  4992.6 1978.13  4997.9 1977.89  5005.2 1976.64  5015.4 1973.65
  5021.2 1971.26  5024.3 1969.47  5024.7 1968.97  5029.7 1968.97  5030.2 1969.47
  5037.1 1970.18  5042.9 1974.16  5050.1 1977.38  5058.8 1978.79  5073.1 1979.24
  5096.0 1978.25  5102.2 1978.69  5161.6 1978.58  5176.2 1978.73  5205.0 1980.10
#Mann=3,-1,0
  4597.4    0.05       0  5024.3    0.05       0  5030.2    0.05       0
Bank Sta=5024.3,5030.2
Exp/Cntr=0.3,0.1

Type RM Length L Ch R = 1,9266,622,622,622
BEGIN DESCRIPTION:
Elm 01 74 9265.42
END DESCRIPTION:
XS GIS Cut Line= 5
      1580715.79      6777600.19      1580806.95      6777795.54
      1580825.88      6777938.36      1580838.20      6778105.43
      1580936.52      6778186.82
#Sta/Elev= 30
  4642.0 1975.91  4676.9 1975.72  4694.2 1974.96  4783.0 1975.35  4805.1 1975.96
  4819.6 1975.64  4827.2 1974.39  4836.9 1974.35  4878.0 1974.95  4956.4 1974.73
  4981.1 1975.18  4991.2 1972.84  4995.9 1968.77  4996.4 1968.27  5001.4 1968.27
  5001.9 1968.77  5011.3 1969.22  5021.3 1975.32  5041.4 1975.15  5057.0 1975.52
  5071.5 1976.57  5081.5 1978.08  5091.5 1977.98  5101.6 1976.67  5121.6 1975.24
  5131.6 1976.06  5190.6 1975.99  5204.0 1976.93  5275.2 1978.25  5296.8 1979.27
#Mann=3,-1,0
  4642.0    0.05       0  4995.9    0.05       0  5001.9    0.05       0
Bank Sta=4995.9,5001.9
Exp/Cntr=0.3,0.1

Type RM Length L Ch R = 1,8644,474,474,474
BEGIN DESCRIPTION:
Elm 01 74 8643.78
END DESCRIPTION:
XS GIS Cut Line= 3
      1580247.06      6777613.29      1580256.00      6777989.94
      1580266.42      6778300.71
#Sta/Elev= 30
  4625.9 1971.33  4690.6 1969.39  4730.6 1969.12  4790.7 1969.33  4810.7 1970.04
  4820.7 1971.68  4830.7 1969.70  4860.7 1970.48  4890.7 1970.18  4920.7 1971.07
  4940.7 1970.99  4970.7 1969.18  4980.7 1967.32  4987.7 1963.66  4988.2 1963.16
  4993.2 1963.16  4993.7 1963.66  5002.7 1964.01  5010.7 1967.09  5020.7 1969.10
  5030.7 1968.67  5048.3 1971.21  5050.7 1971.61  5090.8 1971.54  5123.4 1971.02
  5160.8 1971.22  5190.8 1970.81  5240.9 1971.54  5270.9 1972.33  5313.6 1974.82
#Mann=5,-1,0
  4625.9    0.05       0  4987.7    0.05       0  4993.7    0.05       0
  5048.3    0.12       0  5123.4    0.05       0
Bank Sta=4987.7,4993.7
Exp/Cntr=0.3,0.1

Type RM Length L Ch R = 1,8170,593,593,593
BEGIN DESCRIPTION:
Elm 01 74 8170.09
END DESCRIPTION:
XS GIS Cut Line= 4
      1579885.07      6777199.23      1579817.81      6777774.69
      1579825.44      6778040.29      1579838.74      6778294.15
#Sta/Elev= 30
  4157.0 1967.86  4165.8 1968.16  4195.9 1967.46  4206.1 1966.29  4316.9 1965.19
  4544.3 1965.36  4639.0 1964.94  4789.7 1965.97  4813.6 1967.81  4819.7 1966.74
  4849.7 1967.44  4882.3 1967.25  4919.8 1968.39  4929.8 1968.13  4939.8 1966.88
  4949.8 1966.53  4959.8 1964.12  4976.8 1961.65  4977.3 1961.15  4982.3 1961.15
  4982.8 1961.65  5002.1 1962.14  5009.8 1966.72  5025.3 1966.55  5049.9 1966.68
  5069.9 1968.32  5140.0 1968.05  5170.0 1968.57  5250.1 1970.92  5256.3 1971.66
#Mann=5,-1,0
  4157.0    0.05       0  4882.3    0.12       0  4976.8    0.07       0
  4982.8    0.12       0  5025.3    0.05       0
Bank Sta=4976.8,4982.8
Exp/Cntr=0.3,0.1

Type RM Length L Ch R = 1,7577,332,332,332
BEGIN DESCRIPTION:
Elm 01 74 7577
END DESCRIPTION:
XS GIS Cut Line= 4
      1579168.93      6776850.22      1579290.15      6777149.55
      1579314.71      6777790.17      1579322.88      6778300.67
#Sta/Elev= 30
  4037.1 1958.63  4088.2 1958.57  4093.6 1957.71  4117.8 1957.90  4120.1 1957.03
  4120.6 1956.53  4125.7 1956.53  4126.2 1957.03  4171.4 1957.56  4176.8 1958.13
  4230.4 1959.56  4254.5 1958.92  4598.7 1959.44  4778.8 1960.58  4968.9 1963.03
  4989.0 1957.87  4997.6 1960.01  5001.1 1960.01  5009.0 1962.12  5019.0 1963.55
  5039.0 1964.29  5049.0 1963.99  5069.0 1962.01  5099.0 1962.31  5119.0 1963.56
  5209.0 1963.92  5359.0 1966.19  5469.0 1965.68  5499.0 1964.16  5511.7 1964.62
#Mann=3,-1,0
  4037.1    0.05       0  4120.1    0.03       0  4126.2    0.05       0
Bank Sta=4120.1,4126.2
Exp/Cntr=0.3,0.1

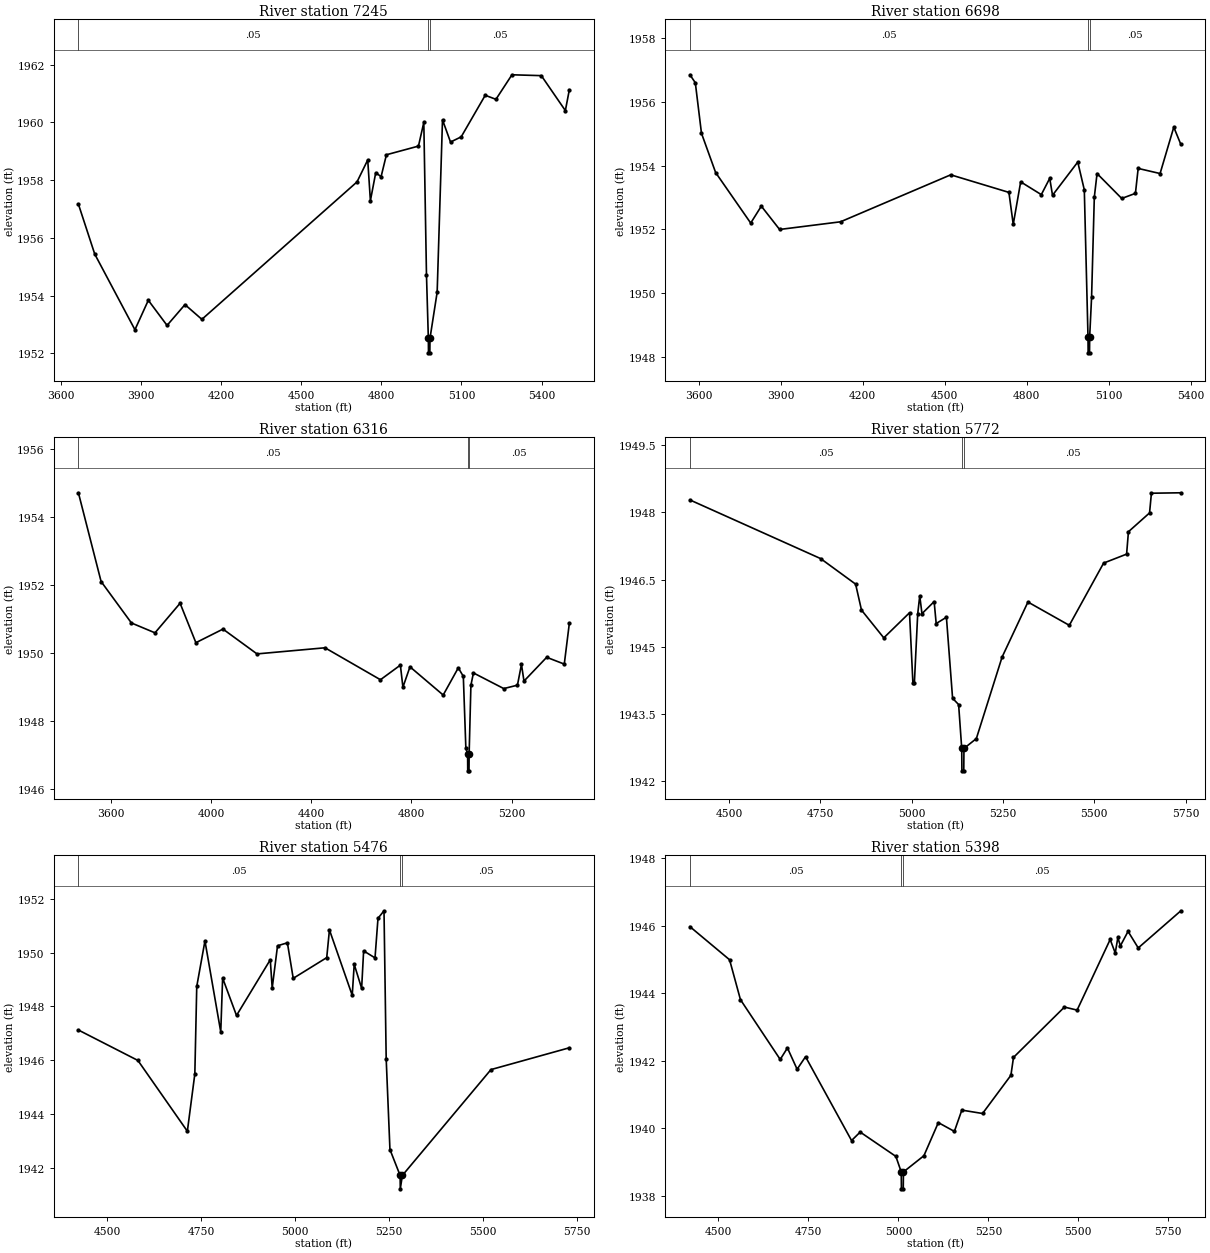
Type RM Length L Ch R = 1,7245,547,547,547
BEGIN DESCRIPTION:
Elm 01 74 7244.93
END DESCRIPTION:
XS GIS Cut Line= 4
      1579030.91      6776456.95      1578970.48      6777238.32
      1578982.68      6777792.34      1578990.95      6778292.91
#Sta/Elev= 30
  3665.7 1957.17  3726.9 1955.44  3877.4 1952.82  3927.5 1953.84  3997.7 1952.97
  4064.8 1953.69  4128.1 1953.18  4709.1 1957.94  4749.2 1958.70  4759.2 1957.29
  4779.2 1958.26  4799.2 1958.12  4819.2 1958.88  4939.2 1959.18  4959.2 1960.00
  4969.2 1954.72  4976.2 1952.52  4976.7 1952.02  4981.8 1952.02  4982.3 1952.52
  5009.2 1954.12  5029.2 1960.09  5059.2 1959.32  5099.2 1959.50  5189.2 1960.94
  5229.3 1960.80  5289.3 1961.65  5399.3 1961.62  5489.3 1960.41  5504.2 1961.13
#Mann=3,-1,0
  3665.7    0.05       0  4976.2    0.03       0  4982.3    0.05       0
Bank Sta=4976.2,4982.3
Exp/Cntr=0.3,0.1

Type RM Length L Ch R = 1,6698,382,382,382
BEGIN DESCRIPTION:
Elm 01 74 6697.93
END DESCRIPTION:
XS GIS Cut Line= 4
      1579017.87      6776433.60      1578515.15      6777459.57
      1578450.34      6777744.05      1578429.56      6778103.86
#Sta/Elev= 30
  3568.6 1956.84  3588.3 1956.59  3610.8 1955.01  3662.6 1953.78  3790.8 1952.20
  3829.6 1952.73  3896.4 1952.00  4119.2 1952.24  4522.0 1953.71  4734.7 1953.16
  4750.5 1952.16  4777.7 1953.49  4853.1 1953.09  4883.9 1953.60  4894.1 1953.07
  4986.4 1954.11  5010.3 1953.24  5023.8 1948.64  5024.3 1948.14  5029.4 1948.14
  5029.9 1948.64  5036.9 1949.88  5046.9 1953.01  5056.9 1953.75  5147.1 1952.97
  5197.2 1953.13  5207.2 1953.91  5287.3 1953.75  5337.4 1955.20  5363.3 1954.66
#Mann=3,-1,0
  3568.6    0.05       0  5023.8    0.05       0  5029.9    0.05       0
Bank Sta=5023.8,5029.9
Exp/Cntr=0.3,0.1

Type RM Length L Ch R = 1,6316,544,544,544
BEGIN DESCRIPTION:
Elm 01 74 6315.8
END DESCRIPTION:
XS GIS Cut Line= 5
      1578853.83      6776350.22      1578130.58      6777332.58
      1578099.82      6777642.49      1578060.70      6777929.37
      1578073.45      6778068.13
#Sta/Elev= 30
  3470.3 1954.70  3560.9 1952.09  3682.0 1950.87  3776.1 1950.58  3876.3 1951.45
  3939.4 1950.29  4047.6 1950.69  4183.4 1949.96  4454.9 1950.14  4676.3 1949.20
  4755.9 1949.63  4766.0 1948.98  4794.2 1949.58  4926.8 1948.75  4987.1 1949.55
  5007.2 1949.30  5017.3 1947.19  5024.3 1947.02  5024.8 1946.52  5029.9 1946.52
  5030.4 1947.02  5037.5 1949.04  5047.6 1949.40  5168.7 1948.94  5223.3 1949.04
  5239.3 1949.65  5249.4 1949.16  5340.0 1949.86  5410.3 1949.66  5430.5 1950.86
#Mann=3,-1,0
  3470.3    0.05       0  5024.3    0.03       0  5030.4    0.05       0
Bank Sta=5024.3,5030.4
Exp/Cntr=0.3,0.1

Type RM Length L Ch R = 1,5772,296,296,296
BEGIN DESCRIPTION:
Elm 01 74 5771.7
END DESCRIPTION:
XS GIS Cut Line= 6
      1578082.13      6777081.99      1577918.33      6777313.04
      1577660.59      6777359.40      1577560.76      6777552.54
      1577808.43      6777812.40      1577842.54      6778031.65
#Sta/Elev= 30
  4393.4 1948.28  4751.1 1946.97  4846.8 1946.40  4862.9 1945.82  4923.9 1945.20
  4994.3 1945.76  5003.6 1944.19  5007.6 1944.19  5016.7 1945.73  5022.3 1946.14
  5028.4 1945.74  5061.7 1946.01  5067.3 1945.52  5095.3 1945.66  5112.2 1943.85
  5128.7 1943.71  5137.2 1942.73  5137.7 1942.23  5142.8 1942.23  5143.3 1942.73
  5177.2 1942.95  5247.6 1944.77  5318.4 1946.00  5431.6 1945.48  5525.5 1946.87
  5588.4 1947.07  5593.4 1947.57  5651.2 1947.99  5656.3 1948.43  5736.9 1948.44
#Mann=3,-1,0
  4393.4    0.05       0  5137.2    0.05       0  5143.3    0.05       0
Bank Sta=5137.2,5143.3
Exp/Cntr=0.3,0.1

Type RM Length L Ch R = 1,5476,78,78,78
BEGIN DESCRIPTION:
Elm 01 74 5476.2
END DESCRIPTION:
XS GIS Cut Line= 6
      1577901.48      6777246.55      1577356.77      6777339.87
      1577354.60      6777417.99      1577500.00      6777472.24
      1577495.66      6777561.22      1577775.64      6777852.05
#Sta/Elev= 30
  4423.5 1947.12  4581.7 1945.99  4713.2 1943.36  4733.1 1945.49  4738.2 1948.74
  4760.0 1950.43  4802.0 1947.05  4807.0 1949.05  4843.9 1947.66  4933.7 1949.73
  4938.8 1948.68  4953.0 1950.25  4979.2 1950.36  4994.7 1949.04  5083.8 1949.81
  5091.0 1950.84  5151.6 1948.41  5156.9 1949.56  5176.6 1948.67  5181.9 1950.06
  5212.2 1949.80  5220.1 1951.27  5236.1 1951.55  5241.9 1946.05  5251.9 1942.68
  5278.9 1941.72  5279.4 1941.22  5285.0 1941.72  5520.5 1945.65  5728.9 1946.46
#Mann=3,-1,0
  4423.5    0.05       0  5278.9    0.05       0  5285.0    0.05       0
Bank Sta=5278.9,5285
Exp/Cntr=0.3,0.1

Type RM Length L Ch R = 1,5398,192,192,192
BEGIN DESCRIPTION:
Elm 01 74 5397.65
END DESCRIPTION:
XS GIS Cut Line= 6
      1577814.66      6777172.77      1577365.45      6777218.34
      1577282.98      6777320.34      1577280.81      6777467.90
      1577400.17      6777543.86      1577738.70      6777901.92
#Sta/Elev= 30
  4420.6 1945.97  4530.8 1944.99  4561.0 1943.81  4671.5 1942.04  4691.6 1942.38
  4718.5 1941.75  4741.9 1942.12  4869.8 1939.64  4893.8 1939.89  4993.0 1939.17
  5007.9 1938.71  5008.4 1938.21  5013.5 1938.21  5014.0 1938.71  5070.9 1939.19
  5111.0 1940.17  5155.6 1939.91  5176.3 1940.54  5233.9 1940.44  5312.7 1941.57
  5319.9 1942.10  5461.5 1943.59  5496.7 1943.50  5588.6 1945.59  5602.7 1945.19
  5610.0 1945.65  5616.9 1945.40  5638.3 1945.83  5666.6 1945.34  5785.1 1946.44
#Mann=3,-1,0
  4420.6    0.05       0  5007.9    0.05       0  5014.0    0.05       0
Bank Sta=5007.9,5014
Exp/Cntr=0.3,0.1

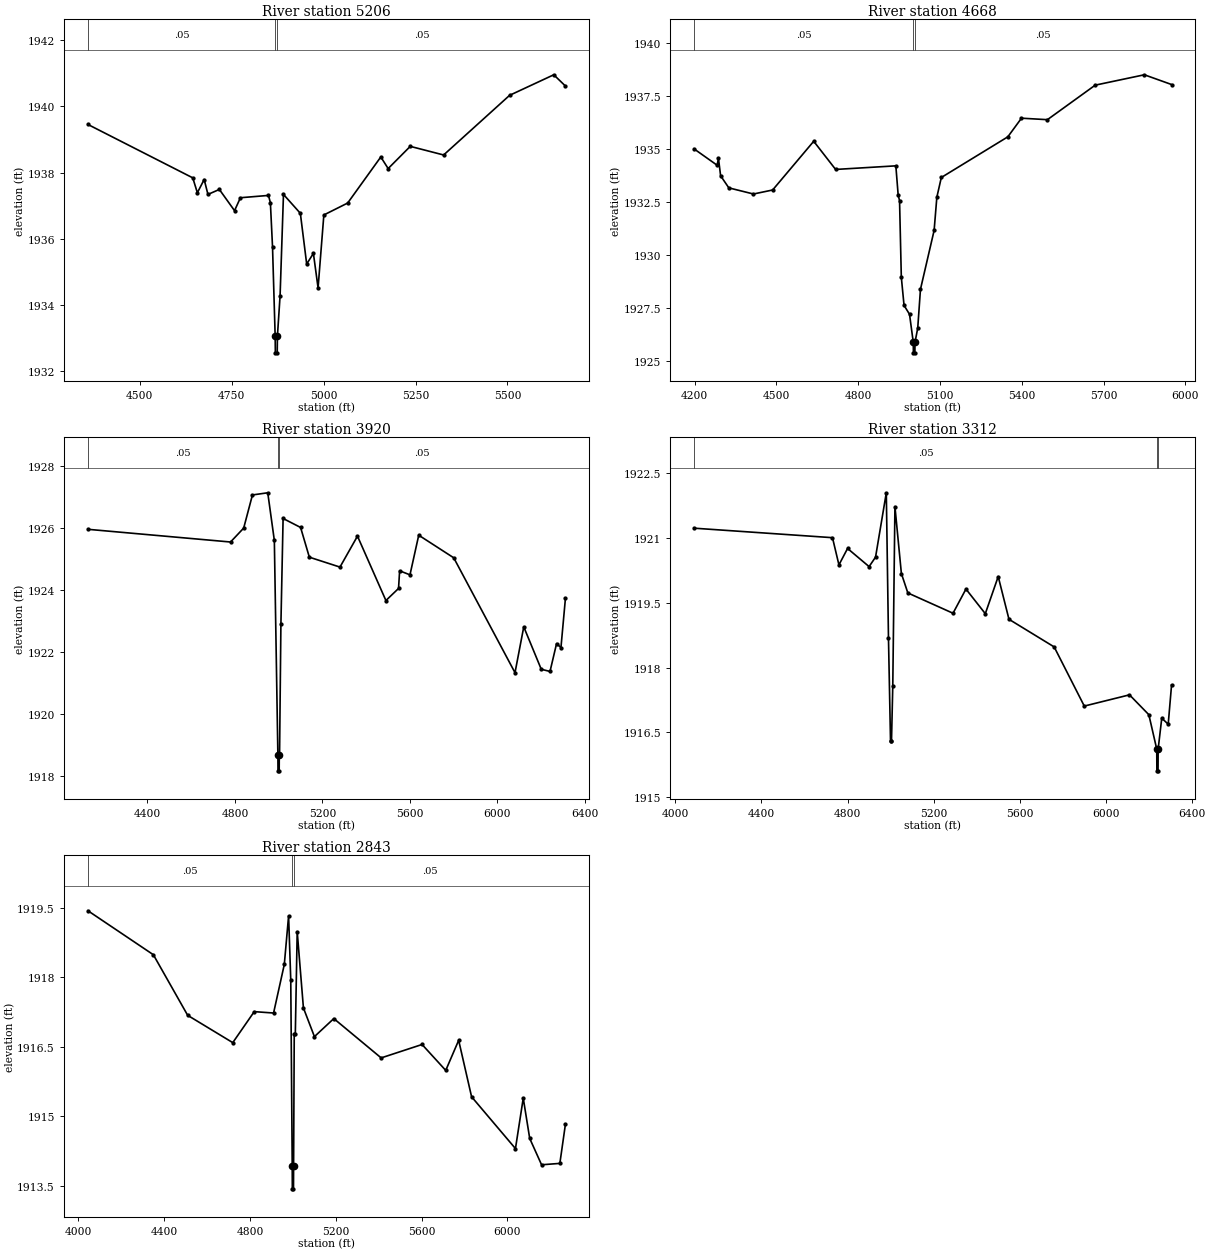
Type RM Length L Ch R = 1,5206,538,538,538
BEGIN DESCRIPTION:
Elm 01 74 5205.81
END DESCRIPTION:
XS GIS Cut Line= 3
      1577263.32      6776661.93      1577103.59      6777283.48
      1577075.81      6777939.75
#Sta/Elev= 30
  4359.2 1939.45  4644.2 1937.84  4656.7 1937.39  4675.2 1937.79  4685.5 1937.34
  4716.5 1937.49  4757.8 1936.85  4773.8 1937.24  4850.1 1937.31  4855.3 1937.09
  4861.1 1935.76  4868.3 1933.06  4868.8 1932.56  4873.9 1932.56  4874.4 1933.06
  4881.7 1934.29  4890.9 1937.34  4936.8 1936.77  4954.0 1935.24  4972.3 1935.56
  4985.0 1934.52  5000.7 1936.72  5065.5 1937.08  5155.6 1938.47  5175.6 1938.12
  5235.7 1938.79  5326.5 1938.53  5505.9 1940.33  5626.0 1940.95  5657.8 1940.61
#Mann=3,-1,0
  4359.2    0.05       0  4868.3    0.03       0  4874.4    0.05       0
Bank Sta=4868.3,4874.4
Exp/Cntr=0.3,0.1

Type RM Length L Ch R = 1,4668,748,748,748
BEGIN DESCRIPTION:
Elm 01 74 4667.74
END DESCRIPTION:
XS GIS Cut Line= 3
      1576652.20      6776141.11      1576725.12      6776946.68
      1576676.51      6777887.66
#Sta/Elev= 30
  4198.2 1935.00  4282.6 1934.23  4287.6 1934.55  4295.5 1933.73  4325.6 1933.16
  4416.0 1932.87  4486.3 1933.06  4636.9 1935.36  4717.2 1934.03  4938.1 1934.20
  4946.7 1932.81  4951.7 1932.56  4958.2 1928.94  4968.2 1927.61  4988.3 1927.19
  5002.0 1925.87  5002.5 1925.37  5007.9 1925.37  5008.4 1925.87  5018.4 1926.54
  5028.4 1928.37  5078.5 1931.15  5088.5 1932.72  5104.9 1933.65  5348.8 1935.57
  5398.9 1936.45  5494.0 1936.38  5669.3 1938.01  5849.5 1938.50  5949.3 1938.04
#Mann=3,-1,0
  4198.2    0.05       0  5002.0    0.03       0  5008.4    0.05       0
Bank Sta=5002,5008.4
Exp/Cntr=0.3,0.1

Type RM Length L Ch R = 1,3920,608,608,608
BEGIN DESCRIPTION:
Elm 01 74 3920.43
END DESCRIPTION:
XS GIS Cut Line= 3
      1575989.01      6776116.80      1576023.73      6776991.82
      1576038.72      6778298.63
#Sta/Elev= 30
  4128.5 1925.96  4780.2 1925.55  4840.3 1926.00  4880.3 1927.07  4950.3 1927.14
  4980.4 1925.60  4996.6 1918.66  4997.1 1918.16  5002.5 1918.16  5003.0 1918.66
  5004.2 1918.66  5010.4 1922.89  5020.4 1926.31  5100.4 1926.02  5140.4 1925.06
  5280.4 1924.74  5360.4 1925.74  5490.4 1923.66  5548.1 1924.05  5553.1 1924.62
  5600.4 1924.49  5640.4 1925.77  5800.4 1925.04  6080.5 1921.33  6120.5 1922.81
  6200.5 1921.44  6240.5 1921.37  6270.5 1922.27  6290.5 1922.14  6311.1 1923.74
#Mann=3,-1,0
  4128.5    0.05       0  4996.6    0.03       0  5003.0    0.05       0
Bank Sta=4996.6,5003
Exp/Cntr=0.3,0.1

Type RM Length L Ch R = 1,3312,469,469,469
BEGIN DESCRIPTION:
Elm 01 74 3311.72
END DESCRIPTION:
XS GIS Cut Line= 3
      1575373.38      6776075.37      1575415.05      6776991.99
      1575444.09      6778293.60
#Sta/Elev= 30
  4086.8 1921.23  4730.1 1921.01  4760.1 1920.38  4800.2 1920.76  4900.3 1920.34
  4930.3 1920.56  4980.3 1922.05  4990.4 1918.68  4999.9 1916.29  5004.4 1916.29
  5010.4 1917.58  5020.4 1921.73  5050.4 1920.18  5080.4 1919.73  5290.4 1919.26
  5350.5 1919.82  5440.5 1919.25  5500.5 1920.11  5550.5 1919.12  5760.6 1918.48
  5900.6 1917.11  6110.7 1917.37  6200.7 1916.91  6237.5 1916.11  6238.0 1915.61
  6243.4 1915.61  6243.9 1916.11  6260.7 1916.83  6290.7 1916.69  6306.3 1917.60
#Mann=3,-1,0
  4086.8    0.05       0  6237.5    0.05       0  6243.9    0.05       0
Bank Sta=6237.5,6243.9
Exp/Cntr=0.3,0.1

Type RM Length L Ch R = 1,2843,468,468,468
BEGIN DESCRIPTION:
Elm 01 74 2842.86
END DESCRIPTION:
XS GIS Cut Line= 3
      1574908.10      6776033.69      1574946.30      6776995.46
      1575049.05      6778254.05
#Sta/Elev= 30
  4045.3 1919.44  4350.0 1918.49  4510.0 1917.18  4720.1 1916.59  4820.2 1917.26
  4910.3 1917.23  4960.3 1918.28  4980.3 1919.33  4990.4 1917.94  4997.2 1913.93
  4997.7 1913.43  5003.1 1913.43  5003.6 1913.93  5006.6 1916.78  5011.6 1916.78
  5020.4 1918.99  5049.4 1917.34  5100.7 1916.72  5191.0 1917.11  5411.7 1916.26
  5602.3 1916.55  5712.7 1915.99  5772.9 1916.64  5833.1 1915.42  6037.6 1914.30
  6073.9 1915.39  6104.0 1914.52  6159.3 1913.95  6244.5 1913.98  6270.6 1914.83
#Mann=3,-1,0
  4045.3    0.05       0  4997.2    0.05       0  5003.6    0.05       0
Bank Sta=4997.2,5003.6
Exp/Cntr=0.3,0.1