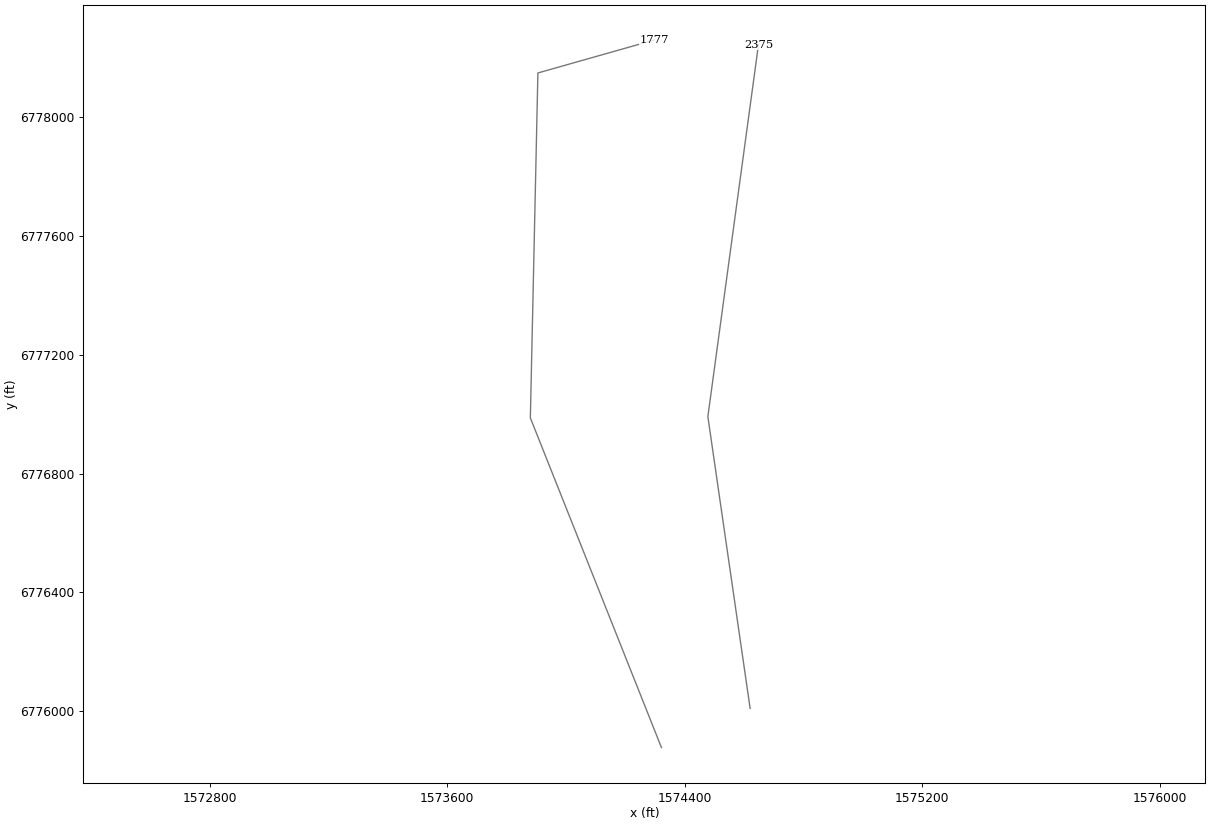
HEC-RAS study Elm 01 74.prj: Elm 01 74 Base Level Engineering

--- Elm 01 74.g01 (geometry) --- (continued)

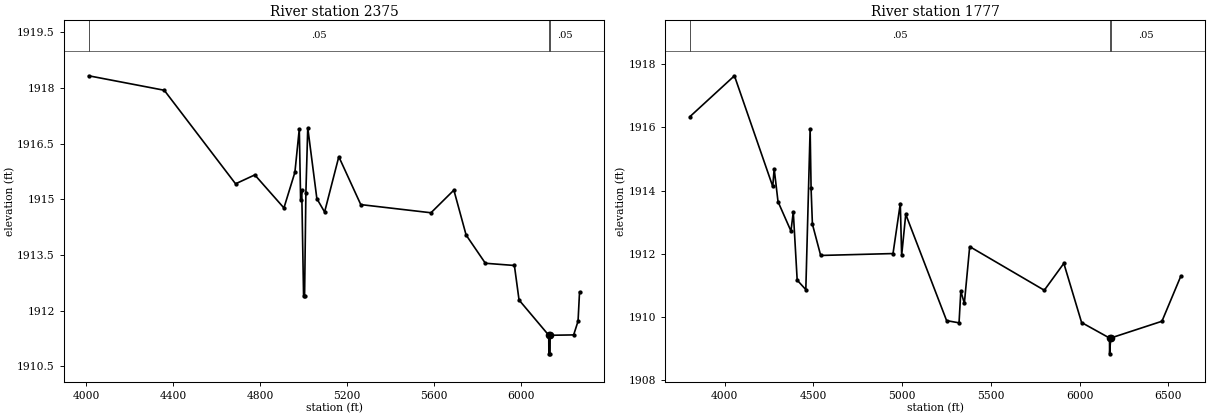
Type RM Length L Ch R = 1,2375,598,598,598
BEGIN DESCRIPTION:
Elm 01 74 2375.04
END DESCRIPTION:
XS GIS Cut Line= 3
      1574619.91      6776009.36      1574477.55      6776991.99
      1574648.01      6778244.76
#Sta/Elev= 30
  4011.5 1918.33  4359.1 1917.94  4687.1 1915.42  4775.5 1915.66  4909.4 1914.77
  4959.9 1915.73  4980.1 1916.90  4986.2 1914.99  4991.3 1915.25  4999.8 1912.40
  5004.4 1912.40  5010.4 1915.17  5019.0 1916.93  5060.9 1915.02  5096.5 1914.66
  5161.8 1916.15  5262.8 1914.86  5585.7 1914.64  5690.9 1915.25  5747.2 1914.04
  5835.7 1913.28  5969.2 1913.22  5990.6 1912.29  6127.2 1911.34  6127.7 1910.84
  6133.1 1910.84  6133.6 1911.34  6241.7 1911.35  6261.9 1911.72  6268.7 1912.50
#Mann=3,-1,0
  4011.5    0.05       0  6127.2    0.05       0  6133.6    0.05       0
Bank Sta=6127.2,6133.6
Exp/Cntr=0.3,0.1

Type RM Length L Ch R = 1,1777,0,0,0
BEGIN DESCRIPTION:
Elm 01 74 4954.683
END DESCRIPTION:
XS GIS Cut Line= 4
      1574321.29      6775877.43      1573879.78      6776987.67
      1573905.19      6778149.27      1574297.57      6778260.39
#Sta/Elev= 30
  3805.2 1916.34  4055.5 1917.63  4271.3 1914.13  4279.3 1914.69  4301.0 1913.65
  4373.9 1912.72  4386.9 1913.33  4408.9 1911.17  4457.5 1910.87  4481.8 1915.95
  4487.2 1914.07  4494.6 1912.94  4541.2 1911.95  4948.6 1912.01  4989.6 1913.59
  4997.2 1911.95  5020.3 1913.25  5250.4 1909.89  5320.4 1909.82  5330.4 1910.82
  5350.4 1910.44  5380.4 1912.23  5800.5 1910.85  5910.6 1911.70  6010.6 1909.83
  6167.8 1909.34  6168.3 1908.84  6174.6 1909.34  6463.1 1909.87  6569.7 1911.30
#Mann=3,-1,0
  3805.2    0.05       0  6167.8    0.05       0  6174.6    0.05       0
Bank Sta=6167.8,6174.6
Exp/Cntr=0.3,0.1

Chan Stop Cuts=-1