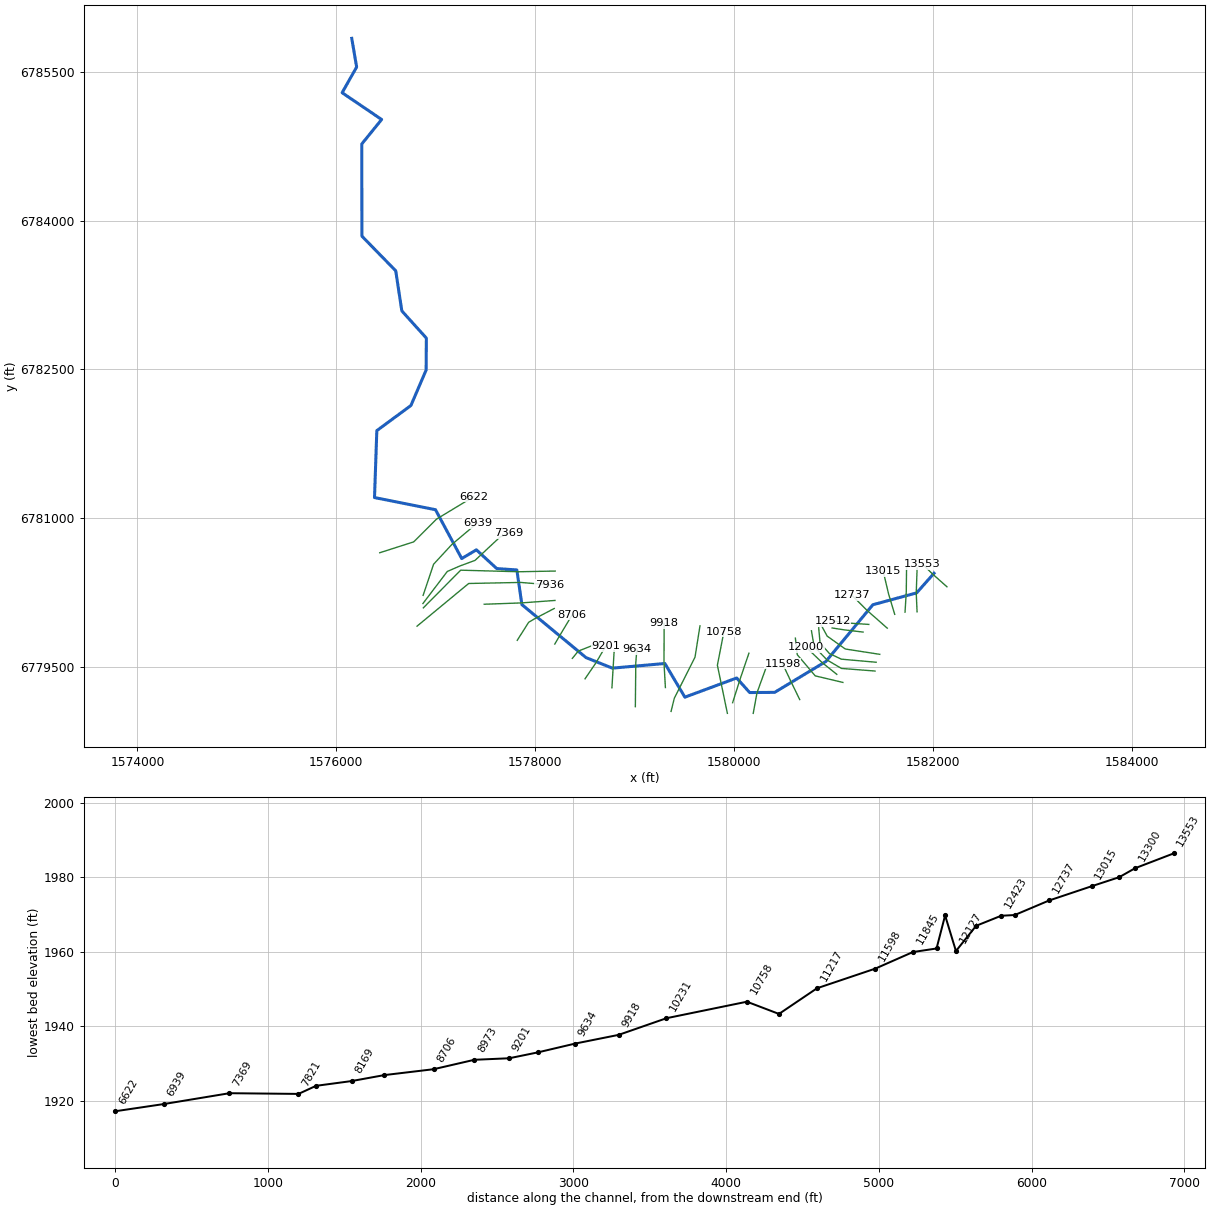
--- Elm 01 75.prj (project) ---

Proj Title=Elm 01 75 Base Level Engineering
Current Plan=p01
Default Exp/Contr=0.3,0.1
English Units
Geom File=g01
Flow File=f01
Plan File=p01
Y Axis Title=Elevation
X Axis Title(PF)=Main Channel Distance
X Axis Title(XS)=Station
BEGIN DESCRIPTION:
Elm 01 75
END DESCRIPTION:
DSS Export Rating Curves= 0
DSS Export Rating Curve Sorted= 0
DSS Export Volume Flow Curves= 0
DXF OffsetX= 0
DXF OffsetY= 0
DXF ScaleX= 1
DXF ScaleY= 10

--- Elm 01 75.p01 (plan) ---

Plan Title=Multiple Run
Short Identifier=Multiple
Geom File=g01
Flow File=f01
Subcritical Flow
K Sum by GR= 0
Std Step Tol= 0.01
Critical Tol= 0.01
Num of Std Step Trials= 20
Max Error Tol= 0.3
Flow Tol Ratio= 0.001
Split Flow NTrial= 30
Split Flow Tol= 0.02
Split Flow Ratio= 0.02
Log Output Level= 0
Friction Slope Method= 1
Unsteady Friction Slope Method= 2
Unsteady Bridges Friction Slope Method= 1
Parabolic Critical Depth
Global Vel Dist=  1 , 1 , 1
Global Log Level= 0
CheckData=True
Encroach Param= -1, 0, 0, 0
BEGIN DESCRIPTION:
Multiple Run
END DESCRIPTION:

--- Elm 01 75.f01 (steady flow) ---

Flow Title=Multiple
Program Version=4.10
Number of Profiles= 7
Profile Names=10-year,25-year,50-year,1pct_min,100-year,1pct_plu,500-year
River Rch & RM=Elm 01 75,Reach-1         ,13553
     174     240     294     225     360     495     545
River Rch & RM=Elm 01 75,Reach-1         ,9634
     561     830    1070     851    1360    1880    2260
River Rch & RM=Elm 01 75,Reach-1         ,9390
     544     792    1010     793    1270    1750    2050
Boundary for River Rch & Prof#=Elm 01 75,Reach-1         , 1
Up Type= 0
Dn Type= 3
Dn Slope=0.005
Boundary for River Rch & Prof#=Elm 01 75,Reach-1         , 2
Up Type= 0
Dn Type= 3
Dn Slope=0.005
Boundary for River Rch & Prof#=Elm 01 75,Reach-1         , 3
Up Type= 0
Dn Type= 3
Dn Slope=0.005
Boundary for River Rch & Prof#=Elm 01 75,Reach-1         , 4
Up Type= 0
Dn Type= 3
Dn Slope=0.005
Boundary for River Rch & Prof#=Elm 01 75,Reach-1         , 5
Up Type= 0
Dn Type= 3
Dn Slope=0.005
Boundary for River Rch & Prof#=Elm 01 75,Reach-1         , 6
Up Type= 0
Dn Type= 3
Dn Slope=0.005
Boundary for River Rch & Prof#=Elm 01 75,Reach-1         , 7
Up Type= 0
Dn Type= 3
Dn Slope=0.005
DSS Import GetInterval= 0
DSS Import GetPeak= 0
DSS Import FillOption= 0

--- Elm 01 75.g01 (geometry) ---

Geom Title=Existing Conditions

River Reach=Elm 01 75,Reach-1
Reach XY= 30
      1582010.13      6780444.49      1581835.26      6780246.57
      1581394.83      6780126.83      1580922.05      6779554.49
      1580407.58      6779243.55      1580156.25      6779241.45
      1580025.28      6779388.39      1579504.78      6779194.99
      1579303.55      6779534.47      1578775.18      6779487.72
      1578510.76      6779593.95      1577865.75      6780128.32
      1577815.18      6780477.68      1577613.15      6780491.57
      1577408.34      6780680.40      1577260.62      6780592.74
      1576997.03      6781085.06      1576383.85      6781207.60
      1576407.07      6781882.53      1576749.55      6782135.53
      1576902.94      6782493.85      1576905.24      6782815.45
      1576658.55      6783089.47      1576597.19      6783494.19
      1576257.00      6783843.30      1576255.75      6784772.99
      1576455.40      6785019.53      1576058.32      6785289.69
      1576204.06      6785548.49      1576155.00      6785838.00

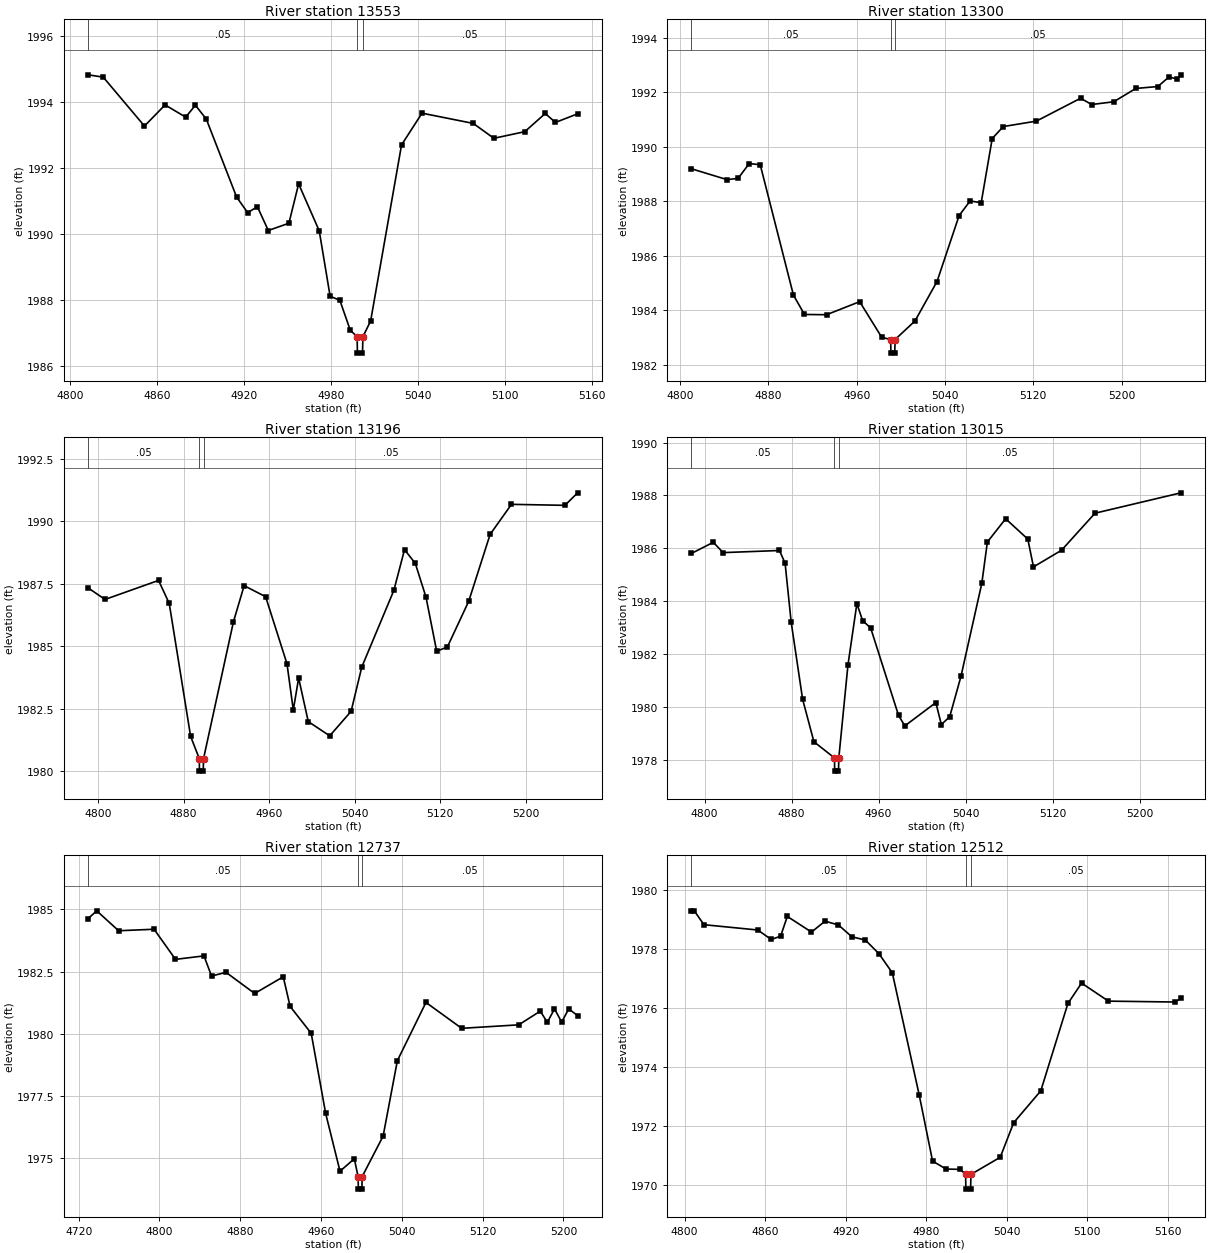
Type RM Length L Ch R = 1,13553,253,253,253
BEGIN DESCRIPTION:
Elm 01 75 13334.685
END DESCRIPTION:
XS GIS Cut Line= 3
      1582139.86      6780308.00      1581999.97      6780432.55
      1581892.43      6780536.98
#Sta/Elev= 30
  4812.7 1994.82  4823.1 1994.75  4851.5 1993.27  4865.7 1993.91  4879.9 1993.54
  4886.6 1993.90  4894.1 1993.48  4915.0 1991.12  4922.6 1990.65  4929.3 1990.83
  4936.8 1990.11  4951.0 1990.33  4957.7 1991.52  4971.9 1990.10  4979.4 1988.12
  4986.1 1988.00  4993.3 1987.09  4998.0 1986.90  4998.2 1986.40  5001.7 1986.40
  5002.0 1986.90  5007.3 1987.37  5028.6 1992.70  5042.7 1993.66  5078.0 1993.35
  5092.2 1992.90  5113.5 1993.10  5127.6 1993.65  5134.6 1993.38  5149.9 1993.64
#Mann=3,-1,0
  4812.7    0.05       0  4998.0    0.05       0  5002.0    0.05       0
Bank Sta=4998,5002
Exp/Cntr=0.3,0.1

Type RM Length L Ch R = 1,13300,104,104,104
BEGIN DESCRIPTION:
Elm 01 75 13299.82
END DESCRIPTION:
XS GIS Cut Line= 3
      1581839.39      6780055.72      1581831.06      6780246.70
      1581840.04      6780498.88
#Sta/Elev= 30
  4810.3 1989.19  4842.6 1988.79  4852.6 1988.84  4862.6 1989.38  4872.6 1989.34
  4902.7 1984.55  4912.7 1983.84  4932.7 1983.83  4962.7 1984.31  4982.7 1983.00
  4990.8 1982.92  4991.0 1982.42  4994.5 1982.42  4994.8 1982.92  5012.8 1983.60
  5032.8 1985.05  5052.8 1987.47  5062.8 1988.01  5072.8 1987.94  5082.8 1990.30
  5092.8 1990.74  5122.8 1990.94  5162.9 1991.78  5172.9 1991.55  5192.9 1991.65
  5212.9 1992.14  5232.9 1992.21  5242.9 1992.56  5250.3 1992.49  5253.8 1992.64
#Mann=3,-1,0
  4810.3    0.05       0  4990.8    0.05       0  4994.8    0.05       0
Bank Sta=4990.8,4994.8
Exp/Cntr=0.3,0.1

Type RM Length L Ch R = 1,13196,181,181,181
BEGIN DESCRIPTION:
Elm 01 75 13196.43
END DESCRIPTION:
XS GIS Cut Line= 3
      1581718.56      6780052.23      1581731.06      6780262.67
      1581733.84      6780509.94
#Sta/Elev= 30
  4790.6 1987.33  4806.4 1986.87  4856.5 1987.63  4866.5 1986.71  4886.5 1981.40
  4894.6 1980.51  4894.8 1980.01  4898.3 1980.01  4898.6 1980.51  4926.6 1985.98
  4936.6 1987.42  4956.7 1986.98  4976.7 1984.30  4982.6 1982.45  4987.6 1983.73
  4996.6 1981.99  5016.7 1981.42  5036.7 1982.40  5046.7 1984.17  5076.7 1987.23
  5086.7 1988.86  5096.8 1988.31  5106.8 1986.96  5116.8 1984.80  5126.8 1984.97
  5146.8 1986.80  5166.8 1989.47  5186.8 1990.67  5236.8 1990.63  5248.7 1991.13
#Mann=3,-1,0
  4790.6    0.05       0  4894.6    0.05       0  4898.6    0.05       0
Bank Sta=4894.6,4898.6
Exp/Cntr=0.3,0.1

Type RM Length L Ch R = 1,13015,278,278,278
BEGIN DESCRIPTION:
Elm 01 75 13015.4
END DESCRIPTION:
XS GIS Cut Line= 3
      1581614.68      6780030.17      1581553.07      6780234.98
      1581498.82      6780464.88
#Sta/Elev= 30
  4787.9 1985.81  4808.0 1986.23  4817.0 1985.84  4868.8 1985.92  4874.0 1985.44
  4879.6 1983.21  4890.1 1980.30  4900.5 1978.69  4919.4 1978.08  4919.6 1977.58
  4923.1 1977.58  4923.4 1978.08  4931.8 1981.59  4940.0 1983.91  4945.3 1983.27
  4952.7 1982.99  4978.3 1979.69  4984.1 1979.29  5012.6 1980.17  5017.7 1979.34
  5025.4 1979.64  5035.7 1981.16  5054.9 1984.68  5060.0 1986.24  5076.8 1987.12
  5097.2 1986.35  5102.4 1985.30  5128.2 1985.93  5159.0 1987.33  5238.0 1988.10
#Mann=3,-1,0
  4787.9    0.05       0  4919.4    0.05       0  4923.4    0.05       0
Bank Sta=4919.4,4923.4
Exp/Cntr=0.3,0.1

Type RM Length L Ch R = 1,12737,225,225,225
BEGIN DESCRIPTION:
Elm 01 75 12736.84
END DESCRIPTION:
XS GIS Cut Line= 3
      1581539.81      6779890.47      1581335.81      6780070.60
      1581186.05      6780221.44
#Sta/Elev= 30
  4729.4 1984.63  4737.9 1984.94  4759.6 1984.14  4794.7 1984.20  4815.9 1982.99
  4844.1 1983.13  4851.6 1982.32  4865.9 1982.47  4894.3 1981.62  4922.6 1982.29
  4929.4 1981.10  4950.3 1980.02  4964.6 1976.80  4978.8 1974.48  4993.0 1974.98
  4996.7 1974.26  4997.0 1973.76  5000.5 1973.76  5000.7 1974.26  5021.5 1975.89
  5035.6 1978.92  5063.9 1981.26  5099.3 1980.22  5155.8 1980.36  5177.1 1980.91
  5184.1 1980.46  5191.2 1981.00  5198.3 1980.47  5205.3 1981.00  5214.1 1980.73
#Mann=3,-1,0
  4729.4    0.05       0  4996.7    0.05       0  5000.7    0.05       0
Bank Sta=4996.7,5000.7
Exp/Cntr=0.3,0.1

Type RM Length L Ch R = 1,12512,89,89,89
BEGIN DESCRIPTION:
Elm 01 75 12511.5
END DESCRIPTION:
XS GIS Cut Line= 3
      1581354.24      6779928.46      1581158.94      6779941.48
      1580991.47      6779963.09
#Sta/Elev= 30
  4805.1 1979.29  4807.2 1979.29  4814.4 1978.82  4854.5 1978.64  4864.5 1978.32
  4871.5 1978.43  4876.5 1979.10  4894.5 1978.57  4904.6 1978.94  4914.6 1978.81
  4924.6 1978.41  4934.6 1978.30  4944.7 1977.84  4954.7 1977.19  4974.7 1973.06
  4984.7 1970.81  4994.8 1970.54  5005.3 1970.53  5009.3 1970.36  5009.5 1969.86
  5013.0 1969.86  5013.3 1970.36  5035.1 1970.94  5045.1 1972.11  5065.3 1973.19
  5085.5 1976.15  5095.7 1976.84  5115.7 1976.23  5165.1 1976.20  5169.7 1976.32
#Mann=3,-1,0
  4805.1    0.05       0  5009.3    0.05       0  5013.3    0.05       0
Bank Sta=5009.3,5013.3
Exp/Cntr=0.3,0.1

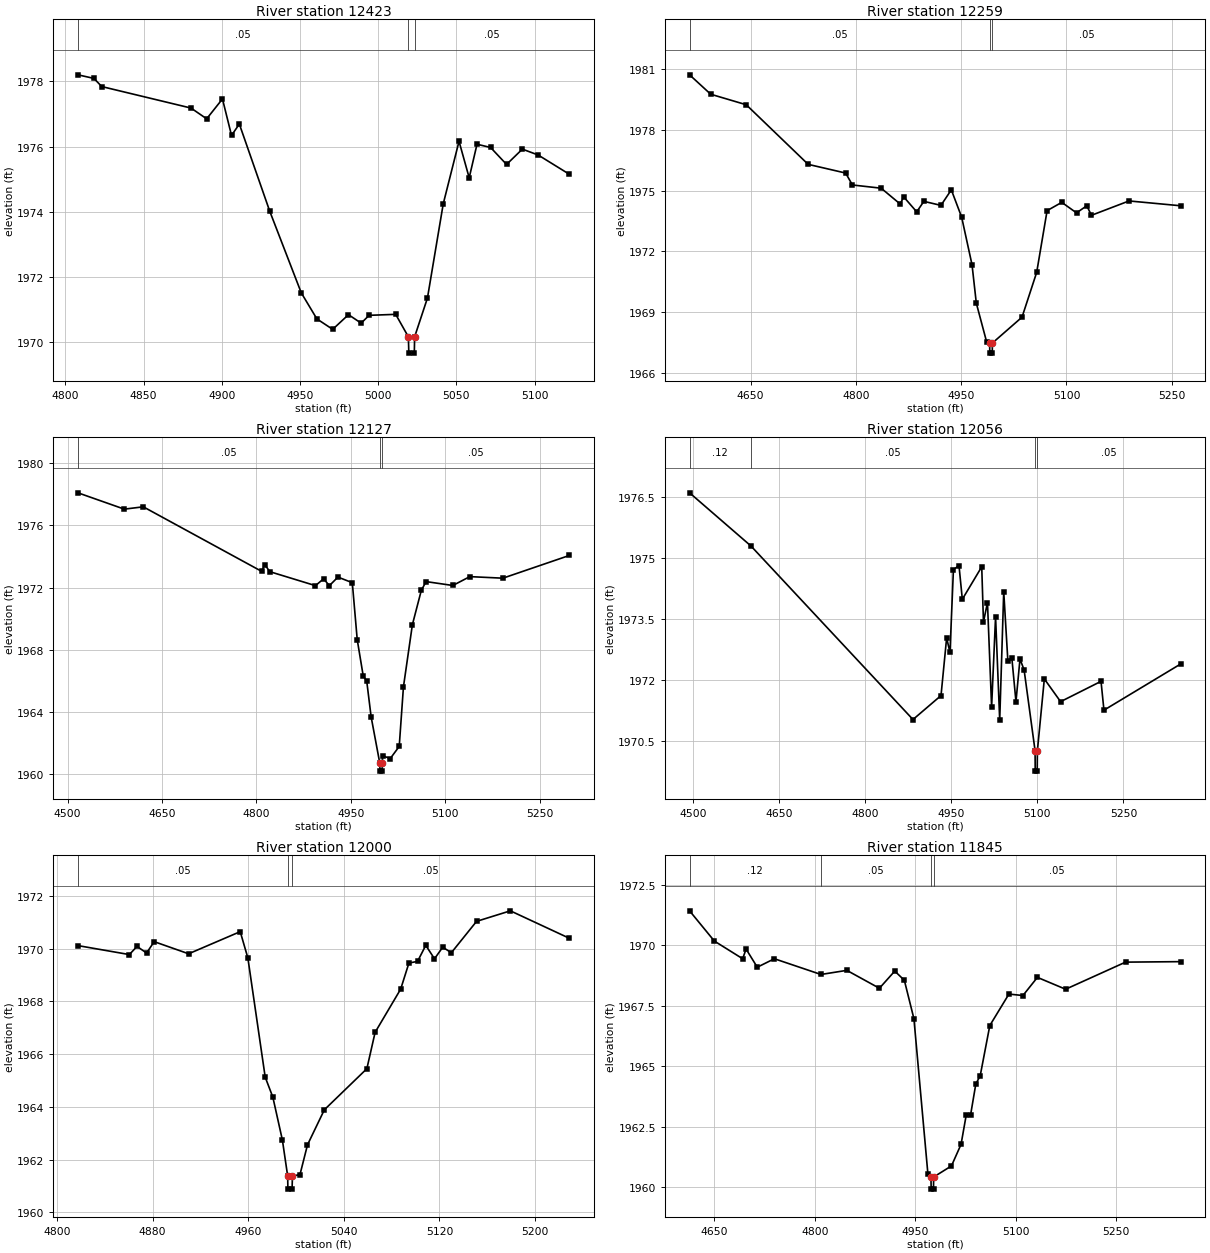
Type RM Length L Ch R = 1,12423,164,164,164
BEGIN DESCRIPTION:
Elm 01 75 12423.41
END DESCRIPTION:
XS GIS Cut Line= 3
      1581296.77      6779851.41      1581103.60      6779874.20
      1580985.34      6779892.65
#Sta/Elev= 30
  4808.0 1978.20  4818.2 1978.09  4823.2 1977.84  4880.3 1977.18  4890.3 1976.85
  4900.4 1977.46  4906.2 1976.34  4911.2 1976.69  4930.6 1974.02  4950.8 1971.51
  4960.8 1970.71  4970.9 1970.39  4981.0 1970.84  4989.1 1970.58  4994.2 1970.82
  5011.2 1970.85  5019.3 1970.16  5019.6 1969.66  5023.1 1969.66  5023.3 1970.16
  5031.5 1971.35  5041.6 1974.24  5051.7 1976.16  5058.2 1975.04  5063.2 1976.07
  5071.9 1975.97  5082.1 1975.45  5092.2 1975.92  5102.3 1975.74  5122.2 1975.15
#Mann=3,-1,0
  4808.0    0.05       0  5019.3    0.05       0  5023.3    0.05       0
Bank Sta=5019.3,5023.3
Exp/Cntr=0.3,0.1

Type RM Length L Ch R = 1,12259,132,132,132
BEGIN DESCRIPTION:
Mapping XS db4f6e0a
END DESCRIPTION:
XS GIS Cut Line= 4
      1581464.72      6779626.80      1581117.49      6779680.62
      1580935.20      6779810.83      1580876.16      6779920.22
#Sta/Elev= 30
  4563.2 1980.73  4593.3 1979.77  4643.9 1979.25  4732.1 1976.30  4785.5 1975.87
  4795.1 1975.28  4836.1 1975.12  4863.1 1974.34  4868.2 1974.69  4886.7 1973.95
  4896.9 1974.47  4921.2 1974.27  4936.0 1975.04  4950.7 1973.69  4965.5 1971.33
  4971.6 1969.43  4986.4 1967.50  4990.5 1967.46  4990.8 1966.96  4994.3 1966.96
  4994.5 1967.46  5036.7 1968.74  5057.6 1970.96  5072.4 1974.01  5093.3 1974.42
  5114.3 1973.90  5128.9 1974.25  5135.6 1973.78  5189.1 1974.49  5262.9 1974.25
#Mann=3,-1,0
  4563.2    0.05       0  4990.5    0.05       0  4994.5    0.05       0
Bank Sta=4990.5,4994.5
Exp/Cntr=0.3,0.1

Type RM Length L Ch R = 1,12127,71,71,71
BEGIN DESCRIPTION:
Elm 01 75 12127.09
END DESCRIPTION:
XS GIS Cut Line= 5
      1581428.29      6779546.98      1581078.55      6779578.07
      1580958.53      6779634.33      1580863.97      6779741.70
      1580850.28      6779894.45
#Sta/Elev= 30
  4516.6 1978.09  4590.2 1977.04  4620.3 1977.19  4808.2 1973.04  4813.2 1973.48
  4821.1 1973.02  4893.7 1972.12  4906.6 1972.56  4915.8 1972.12  4929.4 1972.67
  4952.2 1972.31  4960.0 1968.65  4969.5 1966.32  4975.1 1965.98  4982.1 1963.68
  4995.9 1960.69  4996.1 1960.19  4999.6 1960.19  4999.9 1960.69  5000.3 1961.18
  5012.5 1961.00  5026.7 1961.78  5033.4 1965.61  5047.6 1969.61  5061.8 1971.82
  5069.4 1972.38  5111.8 1972.13  5138.8 1972.70  5191.3 1972.60  5296.7 1974.06
#Mann=3,-1,0
  4516.6    0.05       0  4995.9    0.05       0  4999.9    0.05       0
Bank Sta=4995.9,4999.9
Exp/Cntr=0.3,0.1

Type RM Length L Ch R = 1,12056,56,56,56
BEGIN DESCRIPTION:
Elm 01 75 12056.05
END DESCRIPTION:
XS GIS Cut Line= 5
      1581416.60      6779458.44      1581079.22      6779484.71
      1580934.23      6779570.10      1580804.43      6779705.76
      1580777.49      6779864.47
#Sta/Elev= 30
  4494.5 1976.60  4601.5 1975.29  4883.5 1971.02  4932.3 1971.61  4942.1 1973.03
  4947.9 1972.67  4953.9 1974.71  4963.6 1974.81  4969.4 1973.98  5003.2 1974.78
  5006.2 1973.42  5013.2 1973.90  5020.4 1971.33  5027.3 1973.55  5034.5 1971.00
  5041.5 1974.17  5048.7 1972.46  5055.6 1972.54  5062.8 1971.46  5069.8 1972.51
  5077.0 1972.24  5096.1 1970.25  5096.3 1969.75  5099.8 1969.75  5100.1 1970.25
  5112.2 1972.02  5140.5 1971.46  5210.9 1971.96  5216.0 1971.25  5349.9 1972.39
#Mann=4,-1,0
  4494.5    0.12       0  4601.5    0.05       0  5096.1    0.05       0
  5100.1    0.05       0
Bank Sta=5096.1,5100.1
Exp/Cntr=0.3,0.1

Type RM Length L Ch R = 1,12000,155,155,155
BEGIN DESCRIPTION:
Elm 01 75 11999.65
END DESCRIPTION:
XS GIS Cut Line= 3
      1581032.31      6779425.13      1580889.09      6779539.71
      1580725.01      6779697.71
#Sta/Elev= 30
  4817.5 1970.12  4860.5 1969.78  4866.9 1970.09  4874.9 1969.84  4881.3 1970.27
  4910.1 1969.81  4953.3 1970.65  4959.7 1969.65  4974.2 1965.13  4980.6 1964.37
  4988.6 1962.74  4993.0 1961.38  4993.2 1960.88  4996.7 1960.88  4997.0 1961.38
  5003.3 1961.43  5009.6 1962.56  5023.7 1963.89  5059.3 1965.45  5066.2 1966.83
  5087.6 1968.47  5094.5 1969.46  5101.7 1969.52  5108.6 1970.13  5115.9 1969.62
  5122.8 1970.06  5130.0 1969.85  5151.1 1971.04  5179.4 1971.44  5228.7 1970.40
#Mann=3,-1,0
  4817.5    0.05       0  4993.0    0.05       0  4997.0    0.05       0
Bank Sta=4993,4997
Exp/Cntr=0.3,0.1

Type RM Length L Ch R = 1,11845,247,247,247
BEGIN DESCRIPTION:
Mapping XS a099c4b6
END DESCRIPTION:
XS GIS Cut Line= 4
      1581093.23      6779343.81      1580815.41      6779409.79
      1580634.85      6779623.33      1580615.76      6779789.95
#Sta/Elev= 30
  4613.3 1971.42  4650.3 1970.17  4692.5 1969.44  4697.6 1969.84  4714.3 1969.09
  4739.8 1969.44  4809.3 1968.79  4847.9 1968.96  4896.5 1968.22  4919.4 1968.93
  4933.7 1968.55  4948.0 1966.96  4968.9 1960.53  4973.4 1960.42  4973.7 1959.92
  4977.2 1959.92  4977.4 1960.42  5004.0 1960.88  5018.3 1961.77  5026.0 1962.98
  5032.6 1963.00  5040.3 1964.26  5046.9 1964.61  5061.2 1966.68  5089.7 1967.98
  5110.6 1967.92  5132.2 1968.67  5174.3 1968.18  5263.7 1969.30  5346.2 1969.32
#Mann=4,-1,0
  4613.3    0.12       0  4809.3    0.05       0  4973.4    0.05       0
  4977.4    0.05       0
Bank Sta=4973.4,4977.4
Exp/Cntr=0.3,0.1

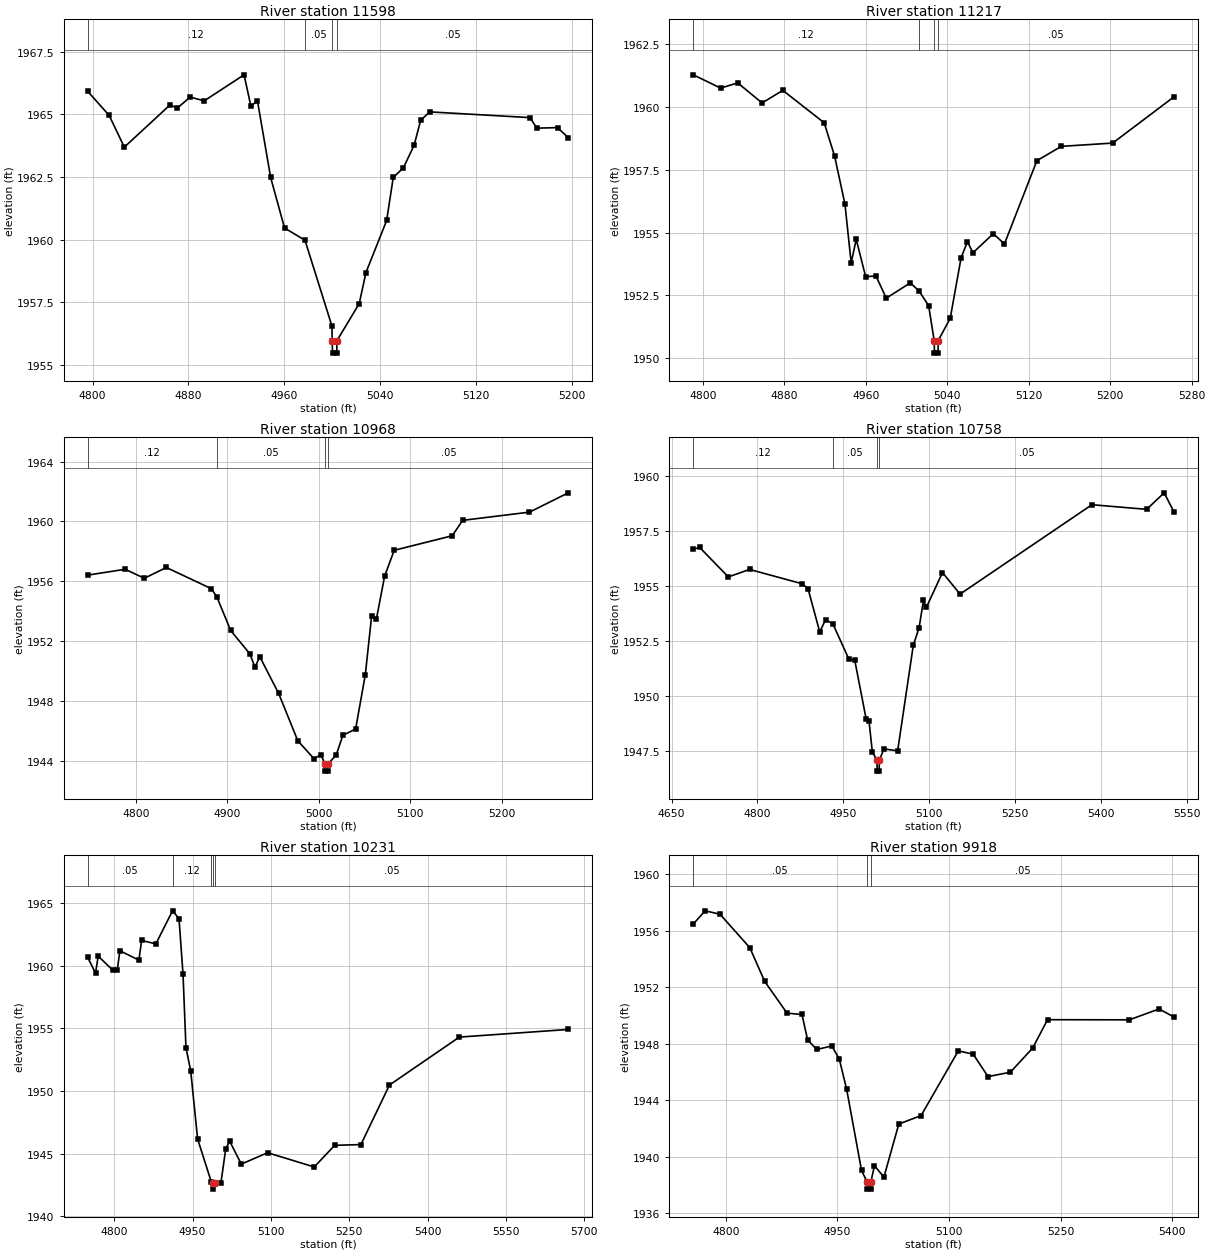
Type RM Length L Ch R = 1,11598,381,381,381
BEGIN DESCRIPTION:
Elm 01 75 11598.19
END DESCRIPTION:
XS GIS Cut Line= 3
      1580659.56      6779170.50      1580569.50      6779356.03
      1580487.03      6779532.92
#Sta/Elev= 30
  4795.9 1965.92  4813.8 1964.96  4826.5 1963.69  4864.5 1965.37  4870.9 1965.26
  4881.5 1965.69  4893.2 1965.54  4926.5 1966.58  4932.2 1965.33  4937.7 1965.54
  4948.7 1962.48  4960.3 1960.46  4977.4 1959.97  4999.9 1956.54  5000.1 1955.96
  5000.4 1955.46  5003.9 1955.46  5004.1 1955.96  5022.7 1957.44  5028.3 1958.68
  5045.6 1960.76  5051.1 1962.48  5059.5 1962.86  5068.5 1963.76  5074.0 1964.76
  5081.5 1965.10  5165.4 1964.87  5171.0 1964.45  5188.3 1964.47  5197.3 1964.07
#Mann=4,-1,0
  4795.9    0.12       0  4977.4    0.05       0  5000.1    0.05       0
  5004.1    0.05       0
Bank Sta=5000.1,5004.1
Exp/Cntr=0.3,0.1

Type RM Length L Ch R = 1,11217,249,249,249
BEGIN DESCRIPTION:
Elm 01 75 11216.62
END DESCRIPTION:
XS GIS Cut Line= 3
      1580191.89      6779031.56      1580229.87      6779238.85
      1580318.26      6779484.60
#Sta/Elev= 30
  4790.6 1961.29  4817.5 1960.76  4834.2 1960.97  4858.1 1960.17  4878.5 1960.67
  4919.1 1959.38  4929.3 1958.06  4939.5 1956.14  4945.6 1953.80  4950.6 1954.73
  4959.8 1953.25  4970.0 1953.27  4980.1 1952.39  5003.7 1953.00  5012.4 1952.67
  5021.7 1952.09  5027.1 1950.70  5027.4 1950.20  5030.9 1950.20  5031.1 1950.70
  5042.9 1951.59  5053.6 1954.01  5059.8 1954.64  5065.2 1954.20  5085.2 1954.96
  5096.1 1954.55  5128.0 1957.87  5152.0 1958.44  5202.4 1958.57  5262.5 1960.41
#Mann=4,-1,0
  4790.6    0.12       0  5012.4    0.05       0  5027.1    0.07       0
  5031.1    0.05       0
Bank Sta=5027.1,5031.1
Exp/Cntr=0.3,0.1

Type RM Length L Ch R = 1,10968,210,210,210
BEGIN DESCRIPTION:
Elm 01 75 10967.88
END DESCRIPTION:
XS GIS Cut Line= 3
      1579984.65      6779139.02      1580061.69      6779382.08
      1580148.51      6779638.19
#Sta/Elev= 30
  4747.3 1956.41  4788.2 1956.80  4809.2 1956.20  4833.3 1956.92  4882.6 1955.50
  4888.6 1954.94  4903.6 1952.71  4924.6 1951.15  4930.2 1950.25  4935.4 1950.96
  4956.0 1948.51  4977.0 1945.34  4994.7 1944.14  5002.3 1944.41  5006.5 1943.81
  5006.8 1943.31  5010.3 1943.31  5010.5 1943.81  5019.1 1944.41  5026.3 1945.71
  5040.2 1946.12  5050.8 1949.75  5057.7 1953.68  5063.0 1953.50  5071.9 1956.34
  5082.4 1958.07  5145.8 1959.04  5157.2 1960.07  5230.3 1960.62  5272.7 1961.91
#Mann=4,-1,0
  4747.3    0.12       0  4888.6    0.05       0  5006.5    0.05       0
  5010.5    0.05       0
Bank Sta=5006.5,5010.5
Exp/Cntr=0.3,0.1

Type RM Length L Ch R = 1,10758,527,527,527
BEGIN DESCRIPTION:
Elm 01 75 10524.99
END DESCRIPTION:
XS GIS Cut Line= 3
      1579932.16      6779031.75      1579831.50      6779517.08
      1579897.11      6779854.71
#Sta/Elev= 30
  4687.9 1956.67  4699.0 1956.75  4749.1 1955.41  4786.2 1955.75  4878.1 1955.10
  4888.3 1954.88  4908.8 1952.91  4919.0 1953.47  4931.7 1953.28  4959.8 1951.67
  4970.0 1951.62  4989.7 1948.98  4994.8 1948.88  5000.7 1947.46  5008.9 1947.09
  5009.1 1946.59  5012.6 1946.59  5012.9 1947.09  5021.1 1947.60  5044.9 1947.51
  5072.2 1952.30  5082.4 1953.11  5090.0 1954.34  5095.1 1954.03  5123.2 1955.61
  5153.9 1954.63  5384.3 1958.69  5479.9 1958.48  5510.5 1959.23  5527.5 1958.37
#Mann=4,-1,0
  4687.9    0.12       0  4931.7    0.05       0  5008.9    0.05       0
  5012.9    0.05       0
Bank Sta=5008.9,5012.9
Exp/Cntr=0.3,0.1

Type RM Length L Ch R = 1,10231,313,313,313
BEGIN DESCRIPTION:
Mapping XS 100fc552
END DESCRIPTION:
XS GIS Cut Line= 4
      1579365.75      6779051.25      1579398.30      6779183.66
      1579606.64      6779598.16      1579656.40      6779914.00
#Sta/Elev= 30
  4749.3 1960.68  4764.3 1959.42  4769.4 1960.78  4797.4 1959.65  4805.8 1959.64
  4810.9 1961.21  4847.3 1960.46  4852.5 1962.03  4879.8 1961.76  4911.7 1964.40
  4924.1 1963.78  4931.8 1959.33  4937.4 1953.47  4946.5 1951.61  4959.7 1946.17
  4986.2 1942.70  4988.8 1942.66  4989.1 1942.16  4993.7 1942.66  5004.4 1942.68
  5013.6 1945.39  5021.1 1945.99  5043.4 1944.16  5093.7 1945.07  5183.0 1943.93
  5222.1 1945.66  5272.3 1945.72  5327.0 1950.48  5460.8 1954.31  5669.3 1954.92
#Mann=5,-1,0
  4749.3    0.05       0  4911.7    0.12       0  4986.2    0.05       0
  4988.8    0.05       0  4993.7    0.05       0
Bank Sta=4988.8,4993.7
Exp/Cntr=0.3,0.1

Type RM Length L Ch R = 1,9918,284,284,284
BEGIN DESCRIPTION:
Elm 01 75 9917.89
END DESCRIPTION:
XS GIS Cut Line= 3
      1579308.82      6779292.12      1579294.94      6779537.59
      1579295.80      6779937.92
#Sta/Elev= 30
  4756.2 1956.47  4772.1 1957.40  4792.1 1957.16  4832.2 1954.79  4852.2 1952.40
  4882.3 1950.15  4902.3 1950.06  4909.9 1948.26  4922.3 1947.58  4942.4 1947.83
  4952.4 1946.92  4962.4 1944.76  4982.4 1939.01  4990.0 1938.19  4990.4 1937.69
  4994.6 1937.69  4994.9 1938.19  4999.8 1939.35  5012.5 1938.54  5032.5 1942.30
  5062.5 1942.90  5112.5 1947.48  5132.5 1947.25  5152.5 1945.66  5182.5 1945.97
  5212.5 1947.68  5232.5 1949.69  5342.5 1949.68  5382.5 1950.45  5402.4 1949.88
#Mann=3,-1,0
  4756.2    0.05       0  4990.0    0.03       0  4994.9    0.05       0
Bank Sta=4990,4994.9
Exp/Cntr=0.3,0.1

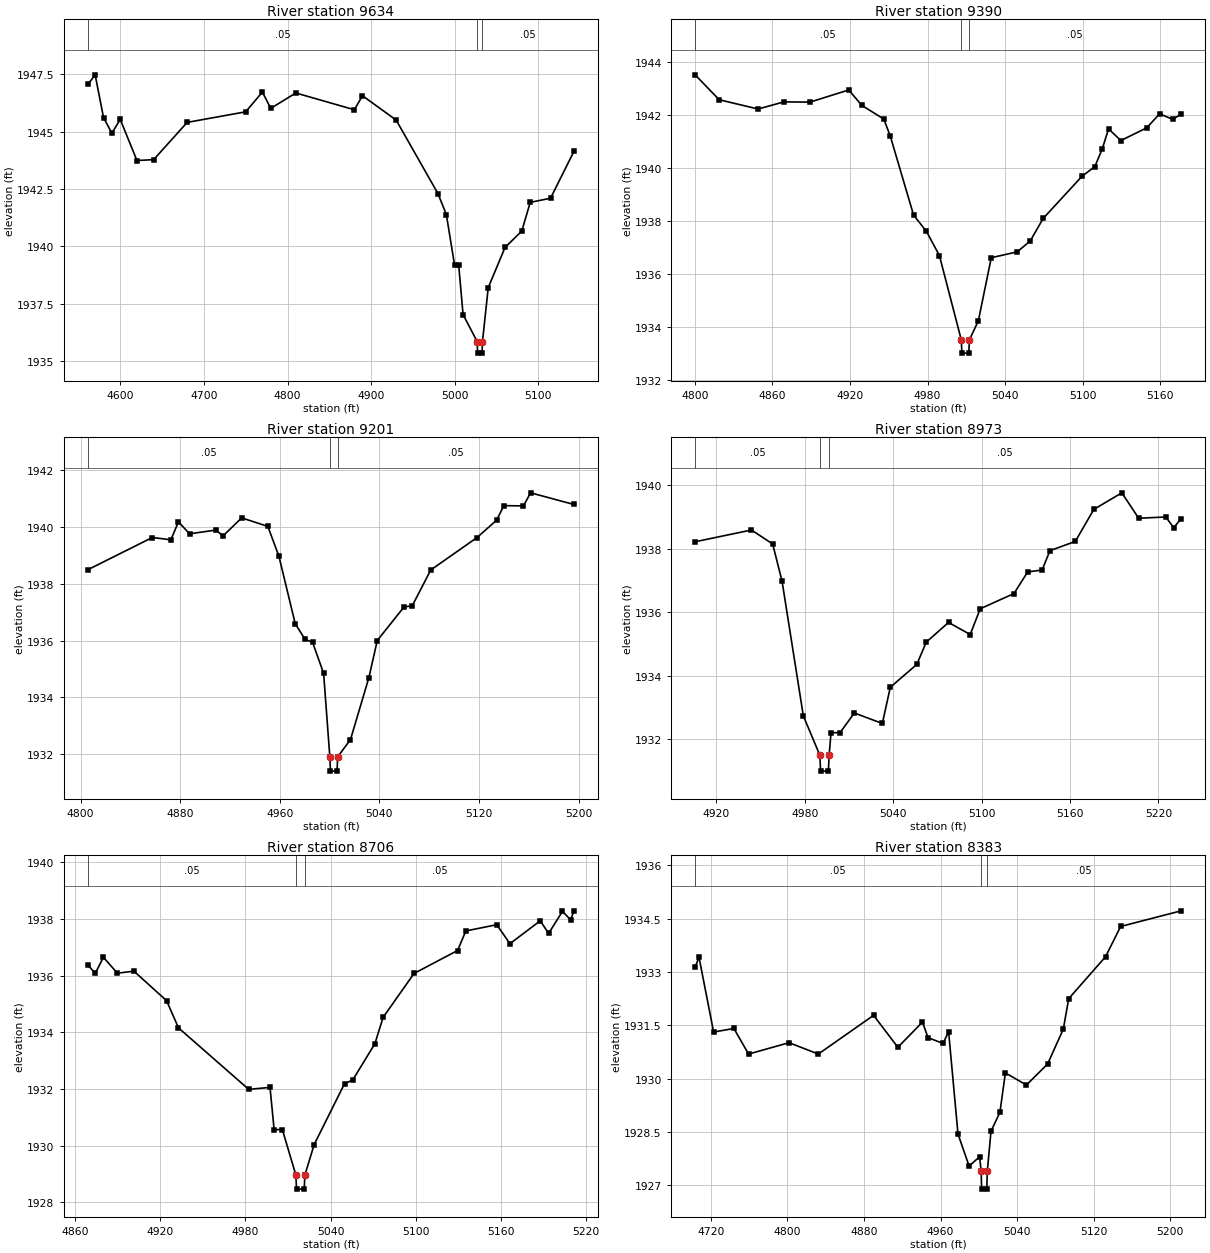
Type RM Length L Ch R = 1,9634,244,244,244
BEGIN DESCRIPTION:
Elm 01 75 9633.5
END DESCRIPTION:
XS GIS Cut Line= 3
      1579006.74      6779099.43      1579011.08      6779542.80
      1579022.36      6779680.15
#Sta/Elev= 30
  4561.3 1947.06  4569.9 1947.47  4579.9 1945.61  4589.9 1944.93  4599.9 1945.53
  4619.9 1943.74  4639.9 1943.78  4679.9 1945.40  4749.9 1945.86  4769.9 1946.72
  4779.9 1946.01  4809.9 1946.68  4879.9 1945.95  4889.6 1946.56  4929.9 1945.50
  4979.9 1942.30  4989.9 1941.39  4999.8 1939.18  5004.7 1939.18  5009.9 1937.04
  5026.8 1935.86  5027.3 1935.36  5032.6 1935.36  5033.1 1935.86  5040.0 1938.21
  5060.1 1939.96  5080.1 1940.67  5090.2 1941.92  5114.5 1942.10  5142.5 1944.14
#Mann=3,-1,0
  4561.3    0.05       0  5026.8    0.03       0  5033.1    0.05       0
Bank Sta=5026.8,5033.1
Exp/Cntr=0.3,0.1

Type RM Length L Ch R = 1,9390,189,189,189
BEGIN DESCRIPTION:
Mapping XS a27135d2
END DESCRIPTION:
XS GIS Cut Line= 2
      1578771.15      6779289.40      1578793.62      6779664.53
#Sta/Elev= 30
  4800.3 1943.50  4818.9 1942.56  4849.0 1942.21  4869.0 1942.48  4889.1 1942.47
  4919.1 1942.93  4929.1 1942.35  4946.2 1941.83  4951.2 1941.19  4969.2 1938.21
  4979.2 1937.59  4989.2 1936.68  5006.1 1933.50  5006.6 1933.00  5011.9 1933.00
  5012.4 1933.50  5019.3 1934.22  5029.3 1936.60  5049.3 1936.82  5059.4 1937.23
  5069.4 1938.08  5099.4 1939.67  5109.4 1940.04  5115.0 1940.69  5120.0 1941.46
  5129.5 1941.02  5149.5 1941.50  5159.5 1942.03  5169.6 1941.82  5176.1 1942.02
#Mann=3,-1,0
  4800.3    0.05       0  5006.1    0.05       0  5012.4    0.05       0
Bank Sta=5006.1,5012.4
Exp/Cntr=0.3,0.1

Type RM Length L Ch R = 1,9201,228,228,228
BEGIN DESCRIPTION:
Elm 01 75 9201.19
END DESCRIPTION:
XS GIS Cut Line= 3
      1578500.83      6779380.35      1578611.93      6779543.54
      1578709.17      6779710.23
#Sta/Elev= 30
  4805.9 1938.49  4857.6 1939.62  4872.5 1939.54  4878.6 1940.17  4887.5 1939.75
  4908.5 1939.88  4914.5 1939.68  4929.4 1940.31  4950.4 1940.01  4959.3 1938.96
  4972.4 1936.59  4980.3 1936.04  4986.3 1935.94  4995.2 1934.85  5000.2 1931.91
  5000.7 1931.41  5006.0 1931.41  5006.5 1931.91  5016.8 1932.52  5031.6 1934.70
  5038.3 1936.00  5059.8 1937.18  5066.4 1937.22  5081.3 1938.48  5118.5 1939.62
  5134.2 1940.23  5140.0 1940.74  5155.7 1940.73  5161.5 1941.19  5196.3 1940.78
#Mann=3,-1,0
  4805.9    0.05       0  5000.2    0.05       0  5006.5    0.05       0
Bank Sta=5000.2,5006.5
Exp/Cntr=0.3,0.1

Type RM Length L Ch R = 1,8973,267,267,267
BEGIN DESCRIPTION:
Elm 01 75 8972.99
END DESCRIPTION:
XS GIS Cut Line= 3
      1578373.37      6779586.46      1578433.12      6779659.86
      1578651.83      6779745.97
#Sta/Elev= 30
  4905.7 1938.22  4943.9 1938.59  4958.3 1938.15  4964.7 1936.97  4979.1 1932.74
  4990.3 1931.50  4990.8 1931.00  4996.1 1931.00  4996.6 1931.50  4997.9 1932.21
  5004.0 1932.21  5013.7 1932.83  5032.7 1932.50  5038.1 1933.64  5056.1 1934.36
  5062.5 1935.06  5077.6 1935.68  5092.3 1935.30  5099.1 1936.11  5122.0 1936.59
  5131.3 1937.27  5141.1 1937.33  5146.4 1937.94  5163.6 1938.23  5176.2 1939.24
  5195.2 1939.76  5206.6 1938.96  5225.0 1939.00  5230.4 1938.66  5235.4 1938.95
#Mann=3,-1,0
  4905.7    0.05       0  4990.3    0.05       0  4996.6    0.05       0
Bank Sta=4990.3,4996.6
Exp/Cntr=0.3,0.1

Type RM Length L Ch R = 1,8706,323,323,323
BEGIN DESCRIPTION:
Elm 01 75 8706.33
END DESCRIPTION:
XS GIS Cut Line= 3
      1578196.47      6779730.18      1578262.98      6779843.89
      1578371.41      6780024.62
#Sta/Elev= 30
  4869.0 1936.38  4874.1 1936.08  4879.9 1936.65  4889.7 1936.09  4901.4 1936.16
  4924.4 1935.12  4932.8 1934.16  4982.3 1931.99  4997.3 1932.06  5000.2 1930.57
  5006.0 1930.57  5015.5 1928.97  5016.0 1928.47  5021.4 1928.47  5021.9 1928.97
  5028.4 1930.04  5049.8 1932.19  5055.6 1932.32  5071.2 1933.60  5077.0 1934.53
  5098.8 1936.08  5129.5 1936.89  5135.3 1937.58  5157.1 1937.80  5166.4 1937.13
  5187.8 1937.94  5193.6 1937.49  5203.4 1938.27  5209.2 1937.97  5211.5 1938.29
#Mann=3,-1,0
  4869.0    0.05       0  5015.5    0.05       0  5021.9    0.05       0
Bank Sta=5015.5,5021.9
Exp/Cntr=0.3,0.1

Type RM Length L Ch R = 1,8383,214,214,214
BEGIN DESCRIPTION:
Elm 01 75 8382.86
END DESCRIPTION:
XS GIS Cut Line= 4
      1577818.92      6779767.93      1577933.96      6779950.11
      1578004.47      6779991.46      1578190.99      6780089.03
#Sta/Elev= 30
  4703.6 1933.13  4707.6 1933.42  4722.9 1931.31  4744.1 1931.41  4759.4 1930.69
  4801.7 1931.01  4832.3 1930.69  4890.0 1931.78  4915.4 1930.88  4941.1 1931.59
  4946.9 1931.15  4962.6 1930.99  4968.4 1931.32  4978.2 1928.44  4989.8 1927.54
  5000.8 1927.80  5002.4 1927.39  5002.9 1926.89  5008.3 1926.89  5008.8 1927.39
  5012.7 1928.52  5022.0 1929.05  5027.7 1930.16  5049.7 1929.82  5071.8 1930.41
  5088.2 1931.39  5093.9 1932.25  5132.4 1933.43  5148.1 1934.28  5211.3 1934.72
#Mann=3,-1,0
  4703.6    0.05       0  5002.4    0.05       0  5008.8    0.05       0
Bank Sta=5002.4,5008.8
Exp/Cntr=0.3,0.1

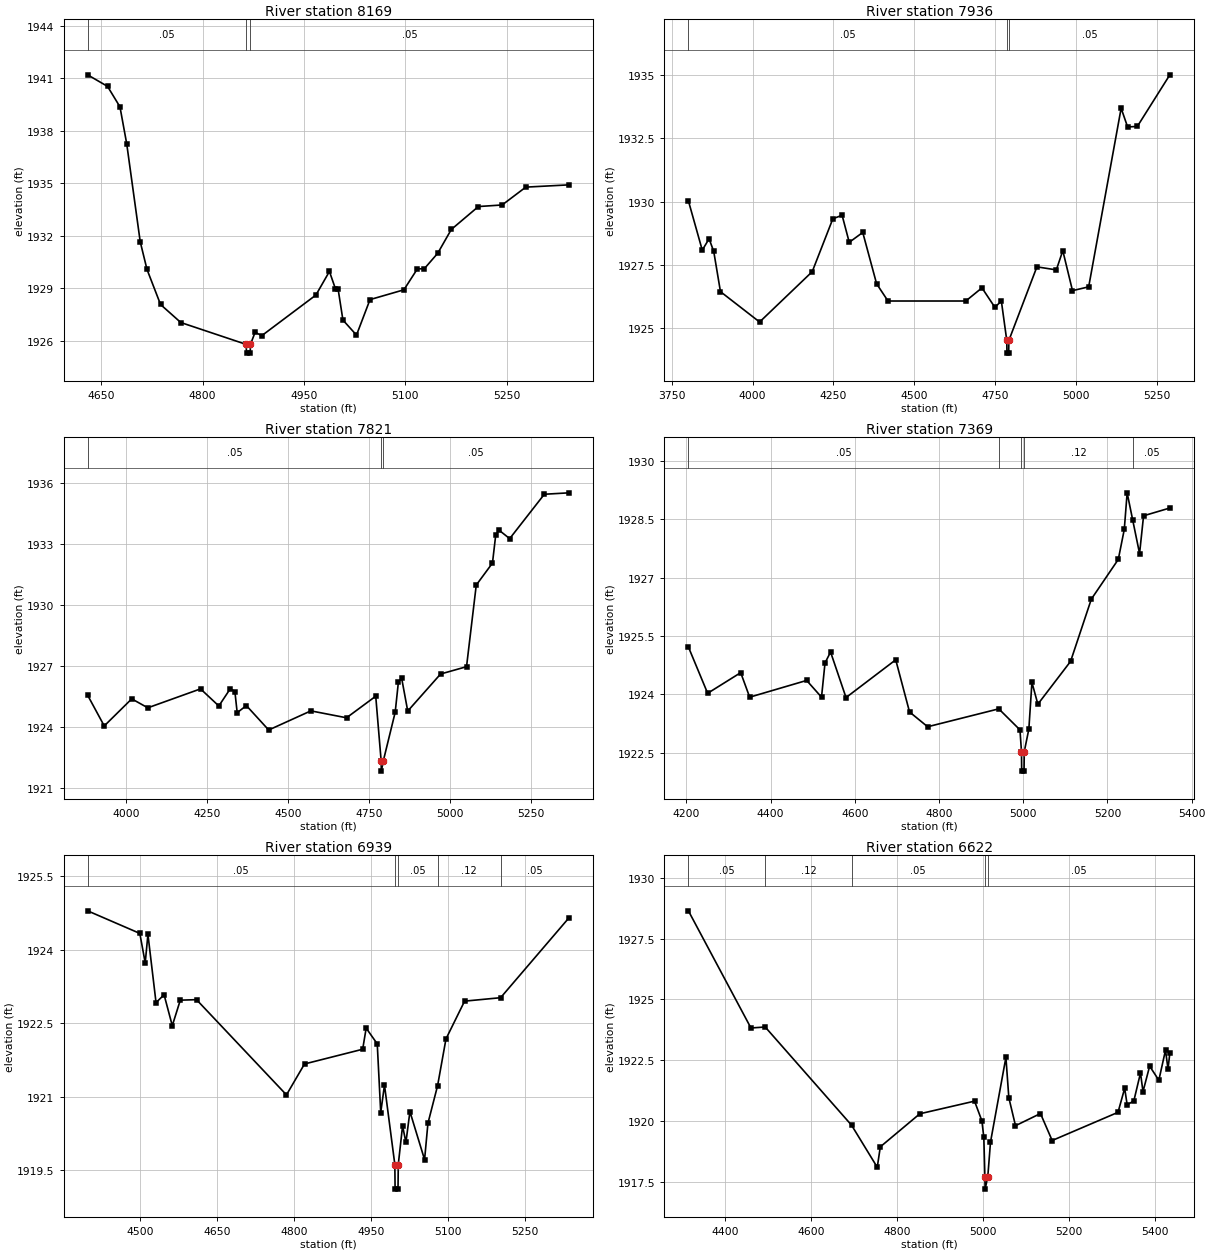
Type RM Length L Ch R = 1,8169,233,233,233
BEGIN DESCRIPTION:
Elm 01 75 8169.36
END DESCRIPTION:
XS GIS Cut Line= 3
      1577487.12      6780132.08      1577857.77      6780145.10
      1578198.96      6780170.28
#Sta/Elev= 30
  4629.6 1941.20  4659.1 1940.54  4677.5 1939.37  4687.5 1937.26  4707.5 1931.66
  4717.5 1930.08  4737.6 1928.07  4767.6 1927.04  4864.4 1925.79  4864.9 1925.29
  4870.3 1925.29  4870.8 1925.79  4877.6 1926.48  4887.6 1926.29  4967.7 1928.61
  4987.7 1929.96  4996.6 1928.97  5000.5 1928.97  5007.7 1927.18  5027.8 1926.32
  5047.8 1928.35  5098.0 1928.91  5118.0 1930.11  5128.1 1930.11  5148.1 1931.00
  5168.2 1932.36  5208.3 1933.67  5243.5 1933.76  5278.5 1934.78  5342.6 1934.91
#Mann=3,-1,0
  4629.6    0.05       0  4864.4    0.05       0  4870.8    0.05       0
Bank Sta=4864.4,4870.8
Exp/Cntr=0.3,0.1

Type RM Length L Ch R = 1,7936,115,115,115
BEGIN DESCRIPTION:
Elm 01 75 7935.7
END DESCRIPTION:
XS GIS Cut Line= 4
      1576811.94      6779911.12      1577330.65      6780341.18
      1577853.60      6780351.93      1578145.22      6780327.63
#Sta/Elev= 30
  3801.3 1930.03  3844.2 1928.08  3865.3 1928.53  3879.7 1928.03  3900.5 1926.44
  4021.6 1925.24  4184.4 1927.23  4248.2 1929.32  4276.8 1929.46  4298.9 1928.39
  4340.7 1928.78  4383.6 1926.75  4418.8 1926.07  4659.5 1926.07  4709.5 1926.59
  4749.5 1925.82  4769.5 1926.07  4786.3 1924.51  4786.8 1924.01  4792.2 1924.01
  4792.7 1924.51  4879.5 1927.42  4939.6 1927.30  4959.6 1928.06  4989.6 1926.48
  5039.7 1926.63  5140.1 1933.69  5160.1 1932.95  5190.2 1932.97  5290.8 1935.01
#Mann=3,-1,0
  3801.3    0.05       0  4786.3    0.05       0  4792.7    0.05       0
Bank Sta=4786.3,4792.7
Exp/Cntr=0.3,0.1

Type RM Length L Ch R = 1,7821,452,452,452
BEGIN DESCRIPTION:
Elm 01 75 7821.33
END DESCRIPTION:
XS GIS Cut Line= 4
      1576874.89      6780095.60      1577250.38      6780475.32
      1577834.50      6780459.57      1578201.28      6780466.49
#Sta/Elev= 30
  3882.4 1925.57  3933.7 1924.06  4018.5 1925.39  4068.1 1924.95  4230.7 1925.88
  4287.2 1925.04  4322.6 1925.89  4336.7 1925.75  4343.8 1924.71  4372.1 1925.06
  4441.0 1923.86  4571.1 1924.80  4681.1 1924.46  4771.2 1925.52  4787.9 1922.34
  4788.4 1921.84  4794.5 1922.34  4831.2 1924.73  4841.2 1926.23  4851.2 1926.40
  4869.9 1924.79  4971.2 1926.61  5051.3 1926.97  5081.3 1930.98  5131.3 1932.06
  5141.3 1933.43  5151.3 1933.68  5184.4 1933.26  5291.3 1935.44  5367.6 1935.51
#Mann=3,-1,0
  3882.4    0.05       0  4787.9    0.05       0  4794.5    0.05       0
Bank Sta=4787.9,4794.5
Exp/Cntr=0.3,0.1

Type RM Length L Ch R = 1,7369,430,430,430
BEGIN DESCRIPTION:
Mapping XS deabc31b
END DESCRIPTION:
XS GIS Cut Line= 6
      1576870.56      6780139.01      1577115.77      6780462.35
      1577240.24      6780516.96      1577394.76      6780574.26
      1577644.76      6780808.63      1577730.79      6780846.48
#Sta/Elev= 30
  4205.0 1925.22  4250.7 1924.03  4329.2 1924.56  4350.5 1923.93  4485.8 1924.36
  4521.1 1923.93  4529.4 1924.81  4542.6 1925.09  4579.3 1923.92  4697.3 1924.89
  4730.1 1923.55  4773.1 1923.17  4942.0 1923.63  4992.3 1923.09  4995.9 1922.53
  4996.4 1922.03  5002.0 1922.03  5002.5 1922.53  5013.4 1923.11  5020.7 1924.31
  5034.8 1923.75  5112.5 1924.85  5161.8 1926.45  5225.8 1927.47  5240.0 1928.24
  5246.8 1929.18  5260.2 1928.47  5276.3 1927.62  5285.8 1928.59  5348.2 1928.79
#Mann=5,-1,0
  4205.0    0.05       0  4942.0    0.12       0  4995.9    0.07       0
  5002.5    0.12       0  5260.2    0.05       0
Bank Sta=4995.9,5002.5
Exp/Cntr=0.3,0.1

Type RM Length L Ch R = 1,6939,317,317,317
BEGIN DESCRIPTION:
Elm 01 75 6938.84
END DESCRIPTION:
XS GIS Cut Line= 4
      1576872.72      6780221.45      1576977.72      6780535.19
      1577161.75      6780734.82      1577418.71      6780951.85
#Sta/Elev= 30
  4397.7 1924.79  4499.5 1924.33  4510.0 1923.73  4515.3 1924.31  4531.1 1922.92
  4546.8 1923.08  4562.8 1922.45  4578.4 1922.97  4610.0 1922.98  4785.4 1921.04
  4820.6 1921.67  4934.0 1921.97  4940.8 1922.40  4962.4 1922.08  4969.2 1920.68
  4976.5 1921.24  4996.7 1919.62  4997.2 1919.12  5002.9 1919.12  5003.4 1919.62
  5011.8 1920.41  5018.3 1920.07  5026.1 1920.70  5054.7 1919.72  5061.2 1920.46
  5080.1 1921.23  5096.4 1922.18  5132.7 1922.95  5202.9 1923.02  5336.4 1924.65
#Mann=5,-1,0
  4397.7    0.05       0  4996.7    0.05       0  5003.4    0.05       0
  5080.1    0.12       0  5202.9    0.05       0
Bank Sta=4996.7,5003.4
Exp/Cntr=0.3,0.1

Type RM Length L Ch R = 1,6622,723,723,723
BEGIN DESCRIPTION:
Elm 01 75 6621.56
END DESCRIPTION:
XS GIS Cut Line= 4
      1576436.50      6780651.14      1576778.13      6780760.93
      1577007.24      6780990.03      1577381.11      6781216.78
#Sta/Elev= 30
  4314.7 1928.64  4460.2 1923.82  4493.4 1923.86  4694.3 1919.82  4754.1 1918.09
  4761.2 1918.93  4853.1 1920.29  4980.4 1920.81  4997.5 1920.00  5002.0 1919.32
  5004.5 1917.69  5005.0 1917.19  5011.2 1917.69  5017.5 1919.12  5053.4 1922.61
  5060.2 1920.95  5075.7 1919.80  5133.8 1920.30  5161.0 1919.19  5314.2 1920.35
  5329.7 1921.34  5335.5 1920.66  5351.0 1920.82  5366.5 1921.97  5372.3 1921.20
  5387.8 1922.25  5409.2 1921.67  5424.7 1922.91  5430.5 1922.13  5434.8 1922.79
#Mann=5,-1,0
  4314.7    0.05       0  4493.4    0.12       0  4694.3    0.05       0
  5004.5    0.05       0  5011.2    0.05       0
Bank Sta=5004.5,5011.2
Exp/Cntr=0.3,0.1