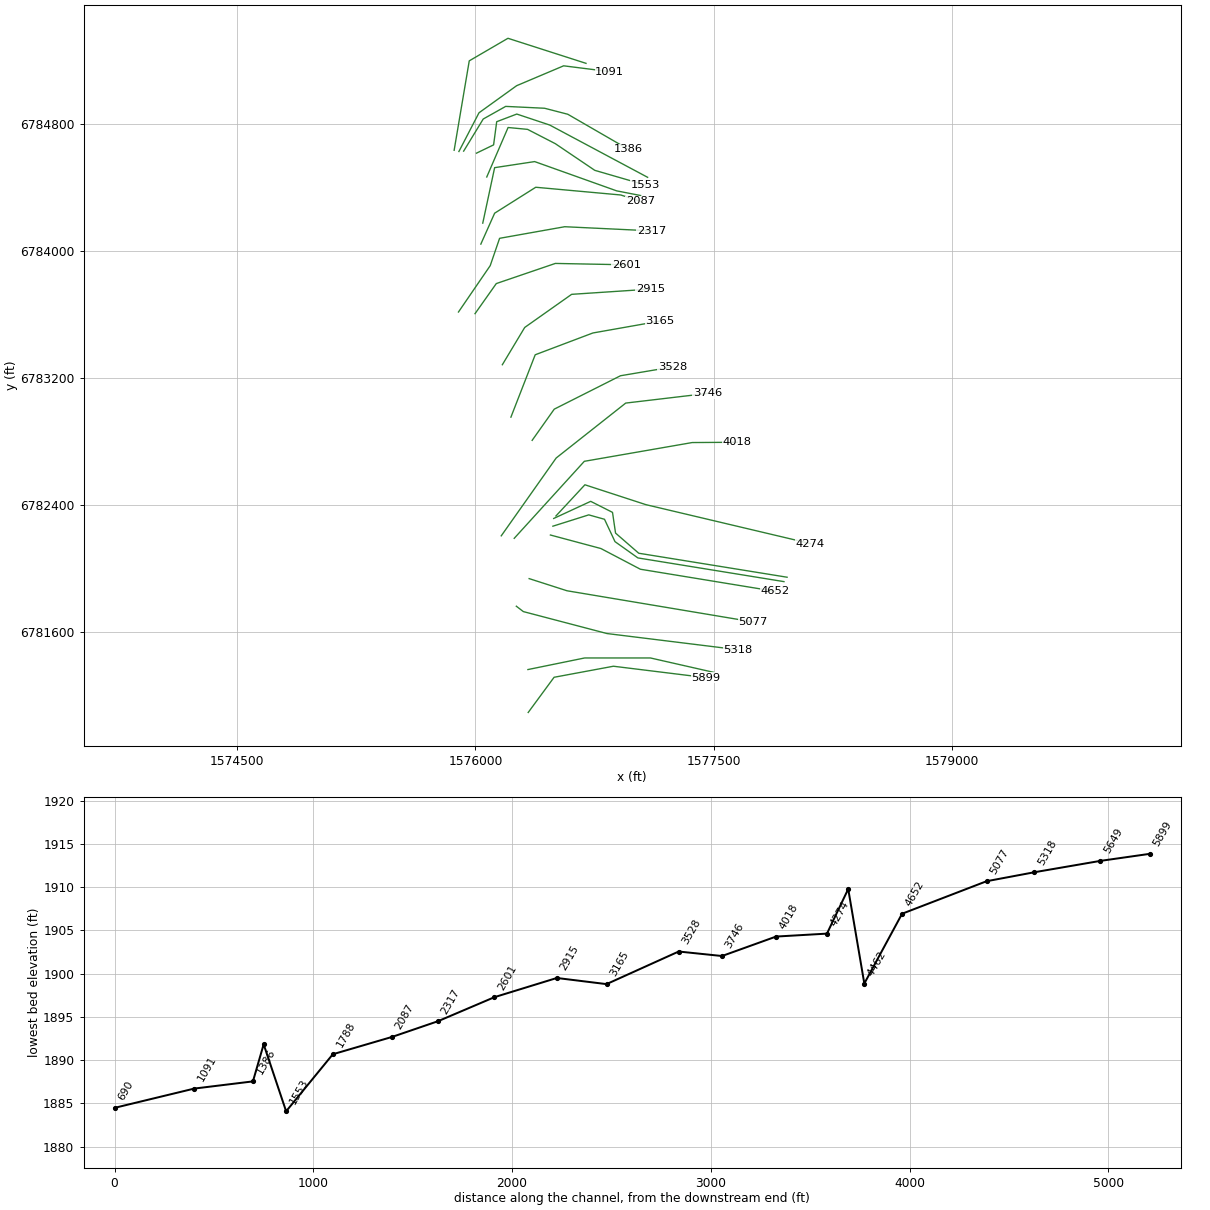
HEC-RAS study Elm 01 75.prj: Elm 01 75 Base Level Engineering

--- Elm 01 75.g01 (geometry) --- (continued)

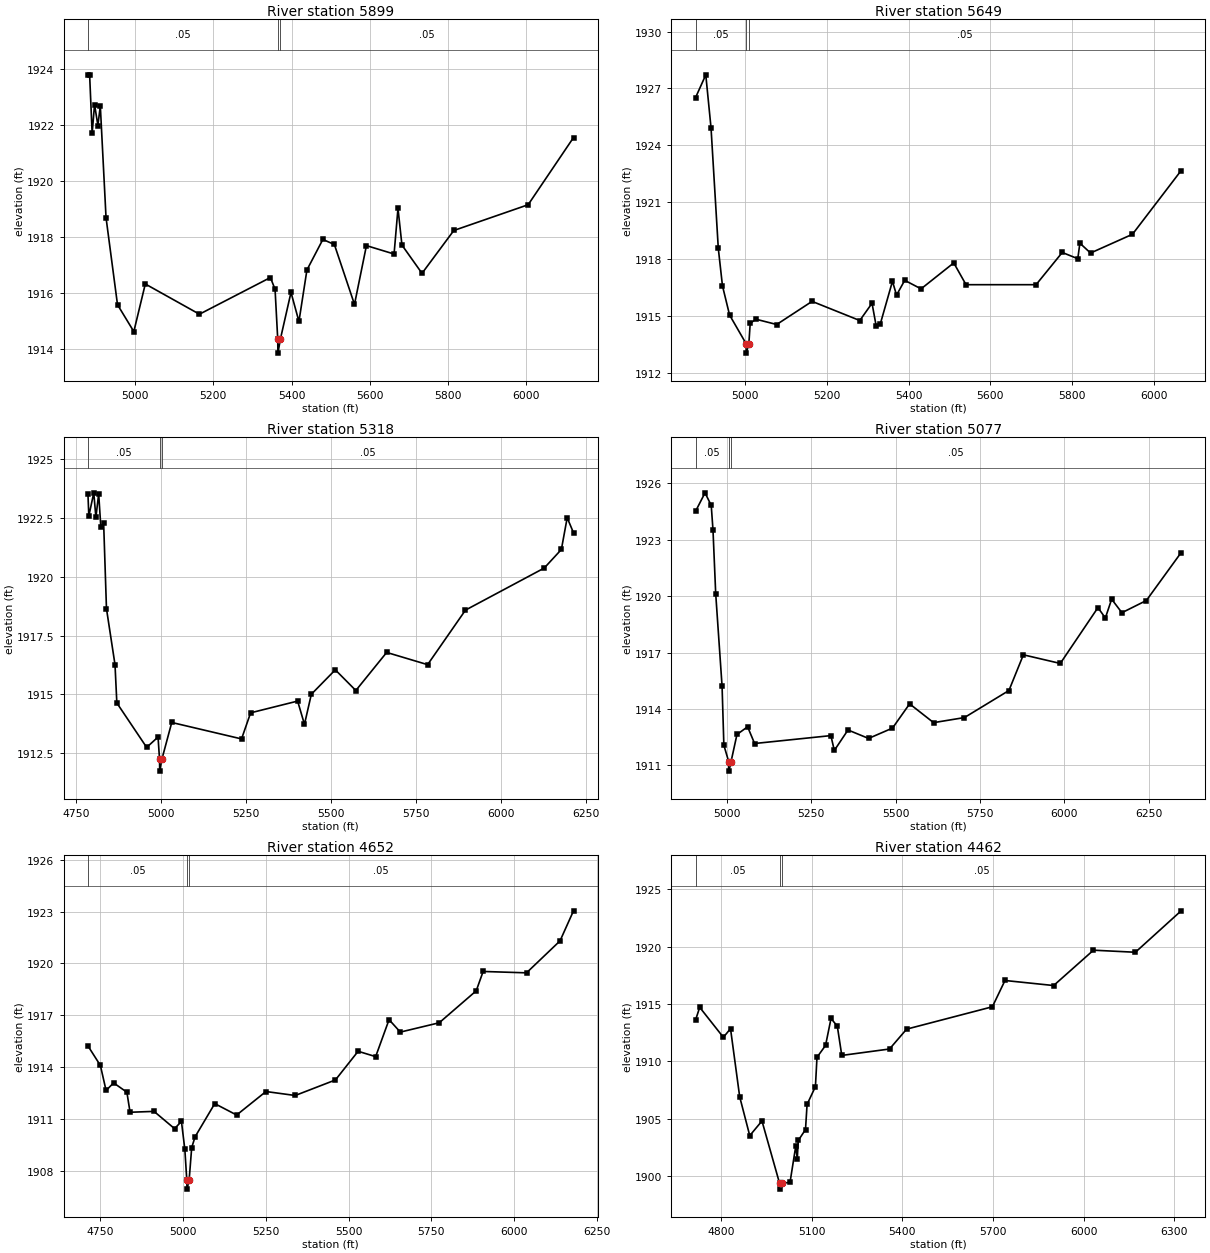
Type RM Length L Ch R = 1,5899,250,250,250
BEGIN DESCRIPTION:
Mapping XS 2500bba7
END DESCRIPTION:
XS GIS Cut Line= 4
      1576332.38      6781096.07      1576495.11      6781317.38
      1576868.38      6781386.83      1577450.01      6781315.21
#Sta/Elev= 30
  4879.7 1923.80  4884.0 1923.80  4890.4 1921.71  4896.6 1922.74  4905.1 1921.99
  4911.3 1922.69  4925.9 1918.70  4955.2 1915.59  4996.9 1914.63  5026.2 1916.33
  5164.5 1915.25  5345.8 1916.56  5357.7 1916.14  5364.5 1914.36  5365.0 1913.86
  5371.3 1914.36  5398.4 1916.03  5418.7 1914.99  5439.1 1916.83  5479.8 1917.92
  5509.2 1917.74  5560.6 1915.60  5591.1 1917.70  5661.7 1917.40  5671.7 1919.03
  5681.8 1917.72  5733.1 1916.71  5814.3 1918.24  6004.2 1919.16  6120.1 1921.56
#Mann=3,-1,0
  4879.7    0.05       0  5364.5    0.05       0  5371.3    0.05       0
Bank Sta=5364.5,5371.3
Exp/Cntr=0.3,0.1

Type RM Length L Ch R = 1,5649,331,331,331
BEGIN DESCRIPTION:
Mapping XS b8c3aa72
END DESCRIPTION:
XS GIS Cut Line= 4
      1576330.53      6781365.92      1576687.29      6781438.84
      1577101.35      6781438.84      1577501.16      6781347.97
#Sta/Elev= 30
  4878.5 1926.52  4903.5 1927.72  4916.3 1924.93  4934.1 1918.57  4944.3 1916.59
  4961.7 1915.05  5002.1 1913.54  5002.6 1913.04  5008.9 1913.54  5012.2 1914.61
  5026.0 1914.83  5077.0 1914.55  5163.6 1915.77  5280.3 1914.76  5310.3 1915.67
  5320.3 1914.49  5330.3 1914.56  5360.3 1916.83  5370.3 1916.10  5390.3 1916.88
  5430.3 1916.43  5510.3 1917.80  5540.3 1916.65  5711.7 1916.65  5775.8 1918.35
  5813.8 1918.02  5818.9 1918.84  5845.0 1918.32  5947.6 1919.31  6066.7 1922.67
#Mann=3,-1,0
  4878.5    0.05       0  5002.1    0.03       0  5008.9    0.05       0
Bank Sta=5002.1,5008.9
Exp/Cntr=0.3,0.1

Type RM Length L Ch R = 1,5318,241,241,241
BEGIN DESCRIPTION:
Mapping XS a36cc574
END DESCRIPTION:
XS GIS Cut Line= 4
      1576257.63      6781764.34      1576301.87      6781730.51
      1576827.92      6781592.48      1577650.43      6781490.97
#Sta/Elev= 30
  4785.3 1923.52  4787.9 1922.58  4802.4 1923.57  4808.7 1922.53  4816.9 1923.53
  4823.2 1922.11  4831.5 1922.27  4839.8 1918.64  4864.9 1916.26  4870.3 1914.63
  4958.0 1912.74  4991.5 1913.18  4995.9 1912.23  4996.4 1911.73  5002.7 1912.23
  5031.8 1913.80  5237.1 1913.10  5263.8 1914.21  5402.1 1914.71  5422.2 1913.72
  5442.4 1915.00  5512.9 1916.04  5573.3 1915.16  5664.0 1916.78  5784.4 1916.26
  5895.8 1918.58  6127.5 1920.37  6177.9 1921.16  6195.0 1922.51  6213.6 1921.87
#Mann=3,-1,0
  4785.3    0.05       0  4995.9    0.05       0  5002.7    0.05       0
Bank Sta=4995.9,5002.7
Exp/Cntr=0.3,0.1

Type RM Length L Ch R = 1,5077,425,425,425
BEGIN DESCRIPTION:
Mapping XS 81123859
END DESCRIPTION:
XS GIS Cut Line= 3
      1576338.30      6781937.98      1576576.18      6781861.58
      1577748.02      6781665.41
#Sta/Elev= 30
  4907.7 1924.52  4935.7 1925.50  4954.1 1924.83  4959.3 1923.52  4967.3 1920.14
  4986.2 1915.20  4991.5 1912.07  5005.9 1911.19  5006.4 1910.69  5012.7 1911.19
  5030.3 1912.64  5061.8 1913.05  5082.5 1912.16  5308.4 1912.58  5318.6 1911.79
  5359.1 1912.88  5420.0 1912.43  5490.9 1912.98  5541.6 1914.27  5612.6 1913.27
  5703.9 1913.54  5835.7 1914.98  5878.5 1916.88  5987.8 1916.42  6099.3 1919.39
  6121.3 1918.84  6139.9 1919.84  6170.3 1919.12  6242.7 1919.77  6345.7 1922.32
#Mann=3,-1,0
  4907.7    0.05       0  5005.9    0.05       0  5012.7    0.05       0
Bank Sta=5005.9,5012.7
Exp/Cntr=0.3,0.1

Type RM Length L Ch R = 1,4652,190,190,190
BEGIN DESCRIPTION:
Mapping XS 72228052
END DESCRIPTION:
XS GIS Cut Line= 4
      1576472.02      6782212.27      1576789.72      6782127.21
      1577037.99      6781997.00      1577885.25      6781858.10
#Sta/Elev= 30
  4712.2 1915.22  4749.8 1914.09  4767.0 1912.64  4789.8 1913.08  4829.9 1912.54
  4839.5 1911.38  4912.0 1911.43  4974.1 1910.43  4994.8 1910.85  5005.1 1909.23
  5011.1 1907.43  5011.6 1906.93  5018.0 1907.43  5025.8 1909.33  5036.1 1909.96
  5095.5 1911.88  5161.7 1911.22  5250.3 1912.58  5338.7 1912.35  5460.3 1913.25
  5528.9 1914.91  5581.9 1914.60  5622.4 1916.74  5656.5 1916.02  5774.1 1916.56
  5885.9 1918.41  5906.8 1919.53  6037.9 1919.45  6139.2 1921.30  6180.0 1923.04
#Mann=3,-1,0
  4712.2    0.05       0  5011.1    0.03       0  5018.0    0.05       0
Bank Sta=5011.1,5018
Exp/Cntr=0.3,0.1

Type RM Length L Ch R = 1,4462,81,81,81
BEGIN DESCRIPTION:
Mapping XS b886a27b
END DESCRIPTION:
XS GIS Cut Line= 6
      1576487.61      6782267.82      1576713.33      6782339.01
      1576812.29      6782311.23      1576878.26      6782170.61
      1577022.36      6782068.18      1577941.28      6781919.07
#Sta/Elev= 30
  4716.3 1913.60  4730.0 1914.70  4808.2 1912.09  4831.9 1912.84  4862.2 1906.91
  4895.5 1903.52  4935.9 1904.80  4994.2 1899.36  4994.7 1898.86  5001.1 1899.36
  5028.8 1899.46  5047.5 1902.58  5052.7 1901.52  5056.0 1903.10  5079.9 1904.05
  5085.1 1906.24  5112.7 1907.79  5117.9 1910.35  5146.2 1911.38  5164.3 1913.73
  5185.1 1913.06  5199.9 1910.51  5357.8 1911.07  5414.3 1912.80  5698.0 1914.75
  5739.7 1917.04  5900.6 1916.60  6032.3 1919.68  6171.0 1919.50  6322.3 1923.11
#Mann=3,-1,0
  4716.3    0.05       0  4994.2    0.03       0  5001.1    0.05       0
Bank Sta=4994.2,5001.1
Exp/Cntr=0.3,0.1

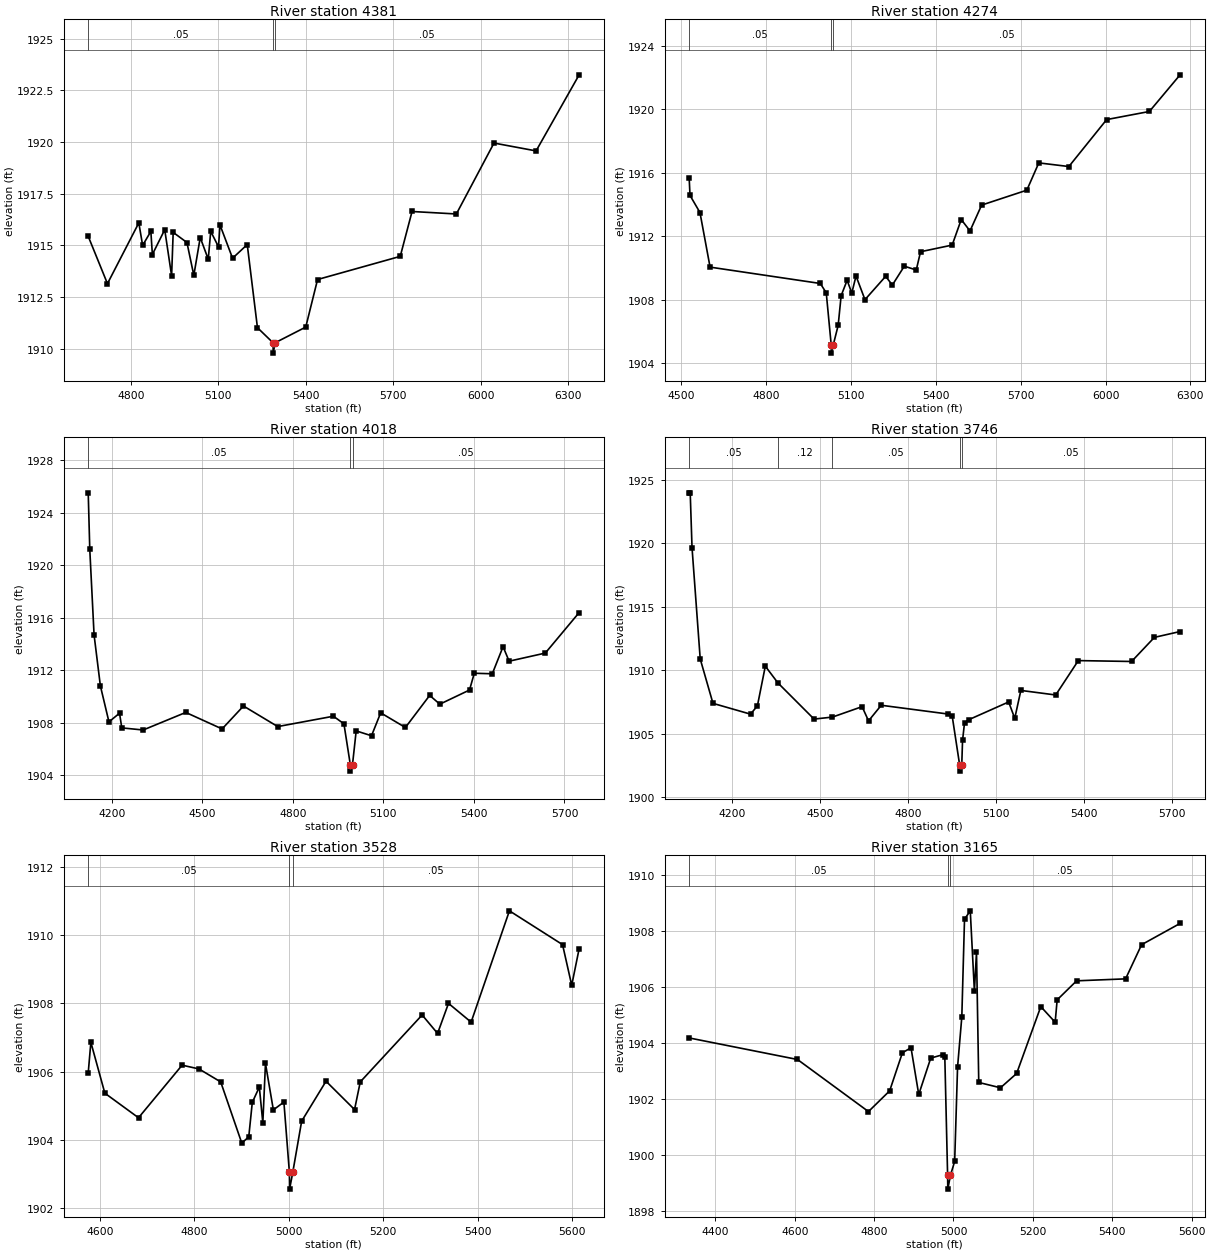
Type RM Length L Ch R = 1,4381,107,107,107
BEGIN DESCRIPTION:
Mapping XS ebfa0787
END DESCRIPTION:
XS GIS Cut Line= 6
      1576492.89      6782316.46      1576725.49      6782424.08
      1576862.64      6782354.64      1576881.74      6782224.43
      1577027.57      6782097.69      1577960.84      6781946.77
#Sta/Elev= 30
  4653.5 1915.44  4719.5 1913.15  4827.1 1916.09  4840.2 1915.00  4868.4 1915.68
  4873.6 1914.56  4916.0 1915.76  4939.6 1913.53  4945.0 1915.63  4992.2 1915.14
  5015.8 1913.55  5037.8 1915.38  5065.3 1914.33  5073.8 1915.68  5100.5 1914.93
  5105.6 1915.99  5148.7 1914.38  5199.1 1915.04  5234.1 1911.02  5287.7 1910.29
  5288.2 1909.79  5294.6 1910.29  5399.8 1911.05  5440.3 1913.35  5724.0 1914.47
  5764.5 1916.64  5916.5 1916.52  6045.6 1919.95  6190.0 1919.57  6337.7 1923.25
#Mann=3,-1,0
  4653.5    0.05       0  5287.7    0.03       0  5294.6    0.05       0
Bank Sta=5287.7,5294.6
Exp/Cntr=0.3,0.1

Type RM Length L Ch R = 1,4274,256,256,256
BEGIN DESCRIPTION:
Mapping XS ad758410
END DESCRIPTION:
XS GIS Cut Line= 4
      1576506.73      6782332.06      1576689.03      6782528.25
      1577072.71      6782403.25      1578107.40      6782158.46
#Sta/Elev= 30
  4528.7 1915.68  4531.7 1914.57  4566.9 1913.49  4602.6 1910.05  4992.1 1909.02
  5013.1 1908.43  5030.7 1905.13  5031.2 1904.63  5037.6 1905.13  5055.2 1906.38
  5065.7 1908.25  5086.8 1909.22  5103.3 1908.42  5118.3 1909.49  5149.9 1908.00
  5223.0 1909.47  5246.6 1908.92  5288.9 1910.11  5331.1 1909.87  5346.3 1911.02
  5458.0 1911.44  5490.1 1913.05  5521.0 1912.33  5562.1 1913.96  5721.8 1914.90
  5764.1 1916.62  5870.3 1916.39  6003.9 1919.35  6154.8 1919.86  6263.3 1922.17
#Mann=3,-1,0
  4528.7    0.05       0  5030.7    0.05       0  5037.6    0.05       0
Bank Sta=5030.7,5037.6
Exp/Cntr=0.3,0.1

Type RM Length L Ch R = 1,4018,272,272,272
BEGIN DESCRIPTION:
Mapping XS 4ad4278d
END DESCRIPTION:
XS GIS Cut Line= 4
      1576244.39      6782191.51      1576685.36      6782675.89
      1577364.18      6782793.94      1577647.13      6782795.68
#Sta/Elev= 30
  4121.7 1925.53  4126.9 1921.21  4141.1 1914.69  4162.0 1910.80  4190.4 1908.05
  4225.5 1908.71  4233.0 1907.59  4303.9 1907.43  4445.1 1908.77  4565.4 1907.51
  4636.3 1909.26  4749.8 1907.69  4934.3 1908.48  4969.2 1907.90  4990.3 1904.79
  4990.8 1904.29  4997.6 1904.79  5009.8 1907.36  5060.6 1906.99  5091.0 1908.74
  5172.9 1907.62  5253.4 1910.07  5287.0 1909.40  5385.4 1910.48  5401.2 1911.76
  5460.9 1911.72  5496.6 1913.79  5516.6 1912.68  5636.6 1913.30  5748.7 1916.39
#Mann=3,-1,0
  4121.7    0.05       0  4990.3    0.05       0  4997.6    0.05       0
Bank Sta=4990.3,4997.6
Exp/Cntr=0.3,0.1

Type RM Length L Ch R = 1,3746,218,218,218
BEGIN DESCRIPTION:
Mapping XS 680875e2
END DESCRIPTION:
XS GIS Cut Line= 4
      1576162.81      6782207.16      1576508.28      6782696.72
      1576945.78      6783042.21      1577459.65      6783102.97
#Sta/Elev= 30
  4053.6 1923.97  4057.2 1923.97  4063.4 1919.64  4091.3 1910.88  4134.8 1907.38
  4262.8 1906.53  4286.3 1907.18  4313.3 1910.31  4356.3 1908.99  4479.6 1906.14
  4542.4 1906.30  4643.3 1907.12  4665.3 1906.00  4708.6 1907.23  4936.3 1906.54
  4950.7 1906.36  4975.9 1902.54  4976.4 1902.04  4983.2 1902.54  4985.9 1904.46
  4992.6 1905.85  5006.8 1906.09  5143.1 1907.49  5163.9 1906.20  5184.7 1908.40
  5303.6 1908.04  5380.6 1910.75  5562.3 1910.68  5640.1 1912.58  5727.7 1913.04
#Mann=5,-1,0
  4053.6    0.05       0  4356.3    0.12       0  4542.4    0.05       0
  4975.9    0.05       0  4983.2    0.05       0
Bank Sta=4975.9,4983.2
Exp/Cntr=0.3,0.1

Type RM Length L Ch R = 1,3528,363,363,363
BEGIN DESCRIPTION:
Mapping XS 7f7fce43
END DESCRIPTION:
XS GIS Cut Line= 4
      1576357.21      6782807.80      1576496.13      6783004.01
      1576912.79      6783214.08      1577240.49      6783269.57
#Sta/Elev= 30
  4575.6 1905.96  4581.2 1906.86  4610.8 1905.37  4682.1 1904.65  4774.4 1906.19
  4810.1 1906.08  4856.1 1905.70  4900.7 1903.91  4915.5 1904.09  4923.0 1905.10
  4937.9 1905.55  4945.3 1904.50  4950.9 1906.24  4967.6 1904.88  4989.9 1905.11
  5001.5 1903.06  5002.0 1902.56  5008.8 1903.06  5027.5 1904.55  5079.1 1905.72
  5139.5 1904.89  5151.6 1905.70  5282.6 1907.66  5315.3 1907.12  5338.4 1908.00
  5386.3 1907.45  5467.4 1910.71  5579.9 1909.72  5599.3 1908.53  5615.0 1909.60
#Mann=3,-1,0
  4575.6    0.05       0  5001.5    0.05       0  5008.8    0.05       0
Bank Sta=5001.5,5008.8
Exp/Cntr=0.3,0.1

Type RM Length L Ch R = 1,3165,250,250,250
BEGIN DESCRIPTION:
Mapping XS bbb6f8d5
END DESCRIPTION:
XS GIS Cut Line= 4
      1576223.57      6782953.70      1576376.33      6783346.03
      1576739.18      6783483.18      1577160.51      6783557.74
#Sta/Elev= 30
  4334.1 1904.19  4607.0 1903.42  4785.8 1901.56  4839.2 1902.30  4871.3 1903.66
  4893.0 1903.84  4912.5 1902.17  4942.7 1903.47  4972.8 1903.59  4978.2 1903.50
  4985.2 1899.29  4985.7 1898.79  4992.5 1899.29  5003.0 1899.78  5010.3 1903.15
  5021.0 1904.94  5027.8 1908.43  5042.3 1908.73  5052.7 1905.87  5058.0 1907.25
  5063.7 1902.60  5118.4 1902.41  5159.1 1902.92  5220.0 1905.31  5256.2 1904.75
  5261.2 1905.55  5310.2 1906.23  5433.6 1906.30  5473.9 1907.52  5570.9 1908.28
#Mann=3,-1,0
  4334.1    0.05       0  4985.2    0.05       0  4992.5    0.05       0
Bank Sta=4985.2,4992.5
Exp/Cntr=0.3,0.1

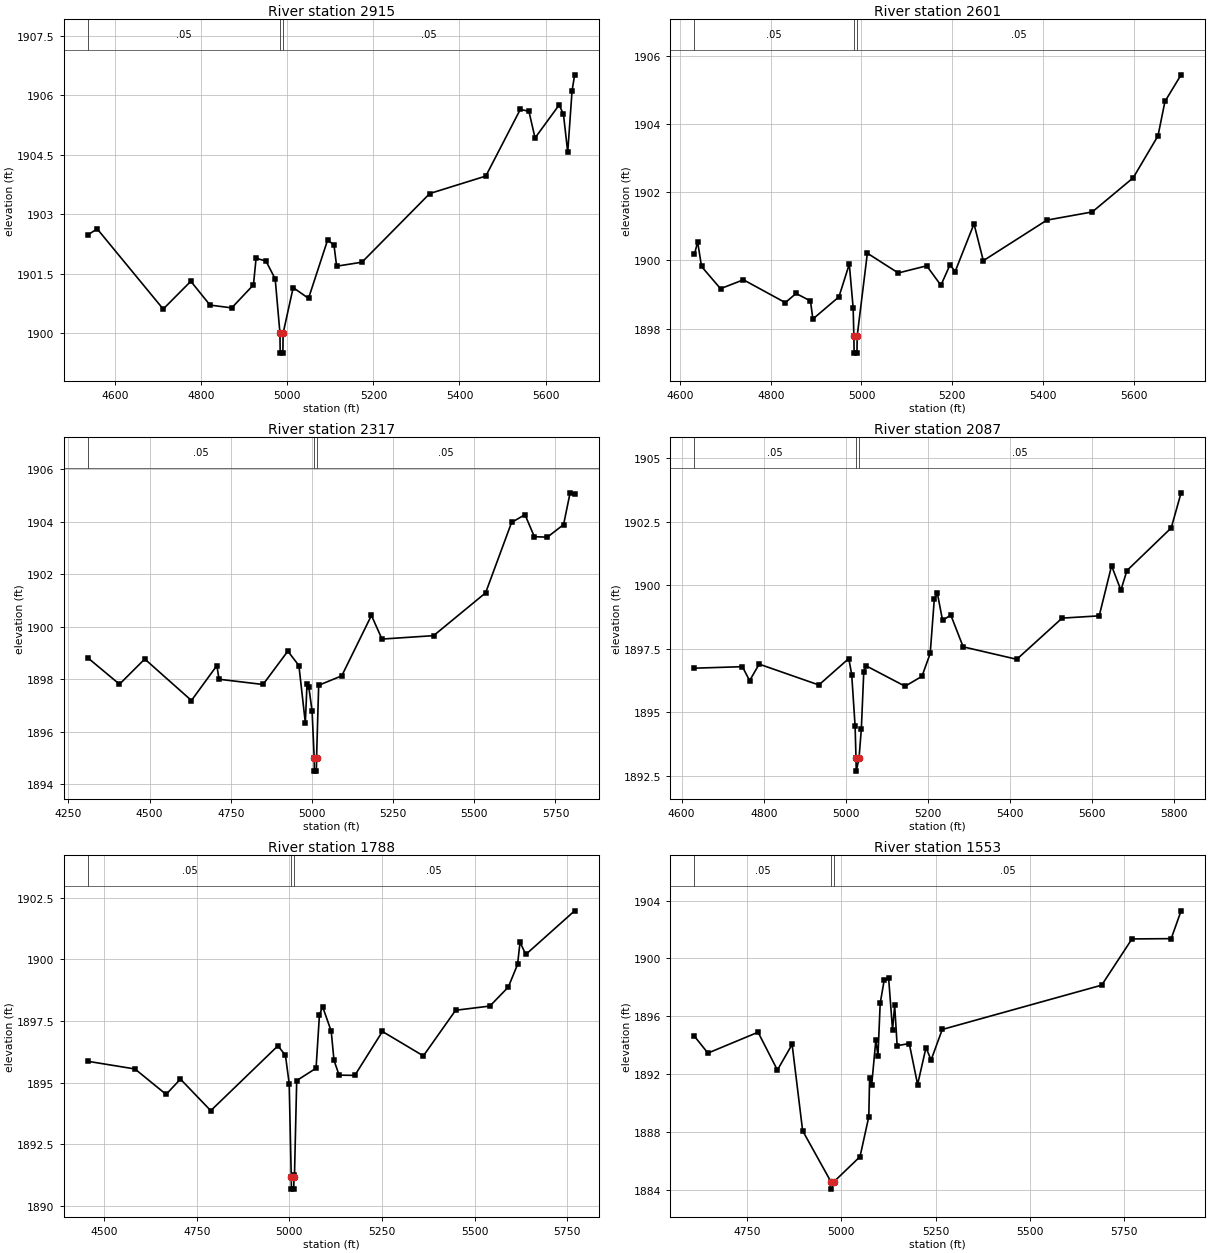
Type RM Length L Ch R = 1,2915,314,314,314
BEGIN DESCRIPTION:
Mapping XS dcc3d8db
END DESCRIPTION:
XS GIS Cut Line= 4
      1576169.76      6783283.57      1576310.36      6783517.90
      1576605.50      6783726.24      1577100.97      6783759.15
#Sta/Elev= 30
  4536.5 1902.48  4557.8 1902.63  4711.3 1900.61  4775.5 1901.31  4820.1 1900.71
  4870.6 1900.64  4921.1 1901.22  4927.2 1901.89  4950.1 1901.82  4971.6 1901.37
  4982.7 1900.00  4983.2 1899.50  4989.5 1899.50  4990.0 1900.00  5013.4 1901.15
  5049.1 1900.88  5093.5 1902.35  5108.3 1902.22  5114.4 1901.69  5173.3 1901.79
  5330.9 1903.52  5461.2 1903.96  5541.4 1905.64  5561.4 1905.59  5575.6 1904.92
  5631.6 1905.75  5641.6 1905.52  5651.6 1904.56  5661.6 1906.10  5667.6 1906.51
#Mann=3,-1,0
  4536.5    0.05       0  4982.7    0.05       0  4990.0    0.05       0
Bank Sta=4982.7,4990
Exp/Cntr=0.3,0.1

Type RM Length L Ch R = 1,2601,284,284,284
BEGIN DESCRIPTION:
Mapping XS a8f7b349
END DESCRIPTION:
XS GIS Cut Line= 4
      1575997.84      6783604.68      1576131.54      6783793.94
      1576503.07      6783920.68      1576950.51      6783912.01
#Sta/Elev= 30
  4632.1 1900.18  4639.1 1900.54  4647.7 1899.82  4689.5 1899.17  4740.0 1899.43
  4832.3 1898.76  4855.8 1899.03  4887.6 1898.81  4892.9 1898.28  4950.3 1898.93
  4973.1 1899.89  4981.6 1898.61  4983.2 1897.78  4983.7 1897.28  4990.0 1897.28
  4990.5 1897.78  5012.9 1900.21  5080.9 1899.63  5143.6 1899.84  5174.9 1899.27
  5195.0 1899.87  5206.2 1899.67  5247.8 1901.07  5268.3 1899.99  5408.3 1901.18
  5508.3 1901.42  5598.4 1902.42  5653.0 1903.65  5668.4 1904.66  5703.9 1905.44
#Mann=3,-1,0
  4632.1    0.05       0  4983.2    0.05       0  4990.5    0.05       0
Bank Sta=4983.2,4990.5
Exp/Cntr=0.3,0.1

Type RM Length L Ch R = 1,2317,230,230,230
BEGIN DESCRIPTION:
Mapping XS 8ff9887f
END DESCRIPTION:
XS GIS Cut Line= 5
      1575893.69      6783615.12      1576093.35      6783906.79
      1576152.38      6784078.67      1576562.10      6784151.58
      1577108.93      6784125.54
#Sta/Elev= 30
  4310.1 1898.81  4407.1 1897.81  4484.9 1898.77  4628.7 1897.19  4707.1 1898.52
  4713.6 1898.00  4849.2 1897.80  4925.6 1899.07  4959.7 1898.52  4979.5 1896.34
  4984.6 1897.81  4990.1 1897.71  5000.3 1896.79  5006.8 1895.00  5007.3 1894.50
  5013.6 1894.50  5014.1 1895.00  5020.6 1897.77  5091.7 1898.13  5183.1 1900.43
  5215.6 1899.53  5374.5 1899.66  5534.7 1901.29  5614.7 1903.97  5656.0 1904.27
  5684.8 1903.43  5724.9 1903.41  5774.9 1903.89  5795.0 1905.10  5808.9 1905.06
#Mann=3,-1,0
  4310.1    0.05       0  5006.8    0.05       0  5014.1    0.05       0
Bank Sta=5006.8,5014.1
Exp/Cntr=0.3,0.1

Type RM Length L Ch R = 1,2087,299,299,299
BEGIN DESCRIPTION:
Mapping XS 863bd482
END DESCRIPTION:
XS GIS Cut Line= 5
      1576034.33      6784042.23      1576121.13      6784236.65
      1576379.81      6784399.85      1576914.53      6784351.24
      1577037.82      6784311.30
#Sta/Elev= 30
  4631.3 1896.74  4748.0 1896.80  4765.7 1896.25  4788.9 1896.90  4934.3 1896.08
  5007.2 1897.12  5014.3 1896.49  5022.5 1894.48  5024.8 1893.19  5025.3 1892.69
  5032.1 1893.19  5037.8 1894.36  5043.7 1896.60  5049.8 1896.83  5144.3 1896.03
  5185.4 1896.42  5205.5 1897.32  5215.5 1899.46  5223.1 1899.68  5235.6 1898.62
  5255.7 1898.83  5285.8 1897.58  5416.4 1897.09  5526.8 1898.71  5617.2 1898.80
  5647.3 1900.77  5670.0 1899.81  5684.7 1900.58  5792.6 1902.26  5816.6 1903.64
#Mann=3,-1,0
  4631.3    0.05       0  5024.8    0.05       0  5032.1    0.05       0
Bank Sta=5024.8,5032.1
Exp/Cntr=0.3,0.1

Type RM Length L Ch R = 1,1788,235,235,235
BEGIN DESCRIPTION:
Mapping XS 44c47c5d
END DESCRIPTION:
XS GIS Cut Line= 5
      1576046.47      6784174.14      1576121.13      6784523.11
      1576372.86      6784561.30      1576888.49      6784377.28
      1577039.57      6784347.76
#Sta/Elev= 30
  4456.6 1895.86  4583.3 1895.55  4667.4 1894.52  4706.0 1895.14  4787.8 1893.86
  4969.1 1896.49  4989.3 1896.10  4999.4 1894.96  5005.0 1891.18  5005.5 1890.68
  5011.8 1890.68  5012.3 1891.18  5013.7 1891.25  5019.7 1895.08  5071.9 1895.58
  5081.0 1897.73  5089.5 1898.08  5112.8 1897.08  5120.3 1895.90  5134.1 1895.30
  5176.5 1895.29  5250.9 1897.07  5361.4 1896.08  5448.5 1897.93  5540.9 1898.10
  5590.6 1898.87  5615.6 1899.79  5622.2 1900.69  5637.7 1900.19  5769.5 1901.96
#Mann=3,-1,0
  4456.6    0.05       0  5005.0    0.05       0  5012.3    0.05       0
Bank Sta=5005,5012.3
Exp/Cntr=0.3,0.1

Type RM Length L Ch R = 1,1553,113,113,113
BEGIN DESCRIPTION:
Mapping XS c92e177f
END DESCRIPTION:
XS GIS Cut Line= 6
      1576071.64      6784464.49      1576205.76      6784775.71
      1576328.16      6784764.00      1576502.64      6784674.15
      1576751.33      6784506.18      1577070.16      6784413.79
#Sta/Elev= 30
  4610.4 1894.63  4646.1 1893.47  4779.1 1894.91  4830.4 1892.30  4869.4 1894.07
  4897.3 1888.11  4972.6 1884.58  4973.1 1884.08  4979.9 1884.58  5049.5 1886.32
  5072.8 1889.08  5074.9 1891.78  5080.5 1891.29  5091.5 1894.37  5097.1 1893.27
  5103.0 1896.90  5113.6 1898.50  5125.5 1898.62  5135.8 1895.06  5141.4 1896.77
  5148.0 1893.98  5180.1 1894.13  5202.3 1891.30  5224.5 1893.85  5238.0 1892.99
  5267.6 1895.10  5690.5 1898.16  5770.8 1901.35  5874.9 1901.37  5901.1 1903.29
#Mann=3,-1,0
  4610.4    0.05       0  4972.6    0.05       0  4979.9    0.05       0
Bank Sta=4972.6,4979.9
Exp/Cntr=0.3,0.1

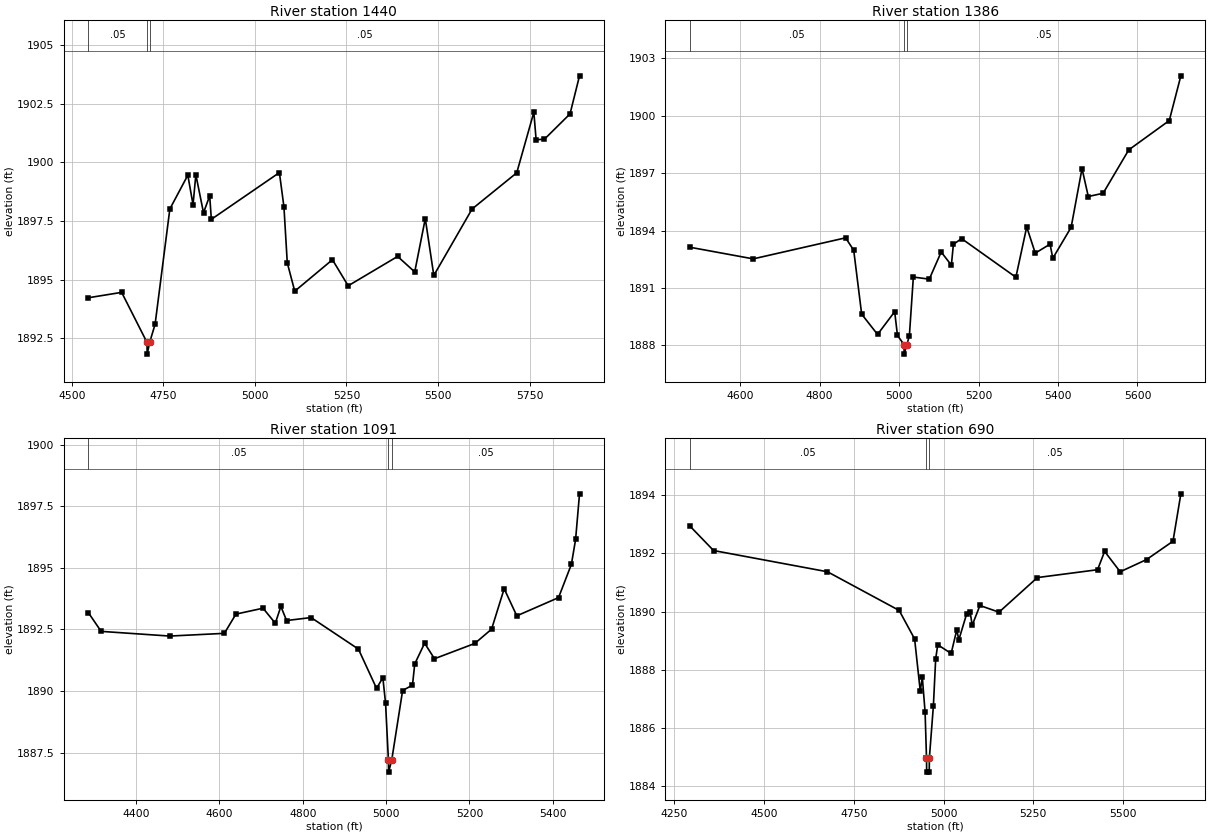
Type RM Length L Ch R = 1,1440,54,54,54
BEGIN DESCRIPTION:
Mapping XS 42bf3285
END DESCRIPTION:
XS GIS Cut Line= 6
      1576006.56      6784614.27      1576114.62      6784666.34
      1576134.15      6784812.17      1576260.45      6784860.35
      1576467.48      6784791.34      1577083.43      6784462.46
#Sta/Elev= 30
  4545.3 1894.23  4636.2 1894.46  4705.4 1892.33  4705.9 1891.83  4712.7 1892.33
  4727.5 1893.10  4767.8 1898.01  4816.9 1899.45  4831.1 1898.19  4838.8 1899.47
  4859.7 1897.85  4876.6 1898.57  4881.1 1897.57  5066.9 1899.56  5079.3 1898.10
  5088.4 1895.72  5108.8 1894.51  5211.7 1895.85  5254.7 1894.74  5389.7 1895.99
  5436.4 1895.33  5465.2 1897.60  5488.5 1895.18  5593.0 1898.01  5714.9 1899.55
  5761.6 1902.13  5767.8 1900.96  5790.4 1900.98  5860.4 1902.06  5886.3 1903.68
#Mann=3,-1,0
  4545.3    0.05       0  4705.4    0.05       0  4712.7    0.05       0
Bank Sta=4705.4,4712.7
Exp/Cntr=0.3,0.1

Type RM Length L Ch R = 1,1386,295,295,295
BEGIN DESCRIPTION:
Mapping XS ac949da7
END DESCRIPTION:
XS GIS Cut Line= 6
      1575926.31      6784627.24      1576049.43      6784829.16
      1576190.66      6784908.53      1576435.45      6784896.81
      1576581.28      6784859.05      1576964.08      6784637.70
#Sta/Elev= 30
  4472.9 1893.13  4632.8 1892.52  4865.4 1893.62  4885.8 1892.97  4905.8 1889.63
  4945.8 1888.57  4988.9 1889.76  4995.9 1888.52  5012.3 1888.04  5012.8 1887.54
  5019.6 1888.04  5025.9 1888.50  5035.9 1891.57  5076.0 1891.46  5106.0 1892.88
  5131.6 1892.19  5136.7 1893.28  5157.3 1893.58  5294.0 1891.56  5321.3 1894.19
  5342.8 1892.82  5380.1 1893.29  5386.9 1892.55  5433.1 1894.17  5460.5 1897.24
  5476.3 1895.78  5513.6 1895.95  5578.2 1898.22  5680.1 1899.75  5709.3 1902.09
#Mann=3,-1,0
  4472.9    0.05       0  5012.3    0.05       0  5019.6    0.05       0
Bank Sta=5012.3,5019.6
Exp/Cntr=0.3,0.1

Type RM Length L Ch R = 1,1091,401,401,401
BEGIN DESCRIPTION:
Mapping XS 6323cf71
END DESCRIPTION:
XS GIS Cut Line= 5
      1575896.38      6784624.67      1576022.69      6784868.16
      1576259.67      6785038.74      1576555.24      6785163.74
      1576844.34      6785127.27
#Sta/Elev= 30
  4285.4 1893.18  4316.1 1892.42  4480.7 1892.23  4611.8 1892.34  4639.5 1893.12
  4704.6 1893.36  4734.0 1892.75  4747.4 1893.43  4761.1 1892.86  4819.9 1892.98
  4933.5 1891.70  4976.9 1890.11  4992.1 1890.54  4998.6 1889.50  5005.4 1887.21
  5005.9 1886.71  5013.5 1887.21  5039.5 1890.02  5063.2 1890.24  5068.6 1891.10
  5092.3 1891.94  5116.0 1891.31  5212.7 1891.93  5253.0 1892.51  5283.2 1894.15
  5313.5 1893.05  5413.7 1893.79  5444.5 1895.14  5454.6 1896.15  5464.0 1898.00
#Mann=3,-1,0
  4285.4    0.05       0  5005.4    0.05       0  5013.5    0.05       0
Bank Sta=5005.4,5013.5
Exp/Cntr=0.3,0.1

Type RM Length L Ch R = 1,690,0,0,0
BEGIN DESCRIPTION:
Elm 01 75 6191.86
END DESCRIPTION:
XS GIS Cut Line= 4
      1575866.44      6784632.47      1575961.49      6785194.99
      1576204.98      6785336.91      1576695.90      6785179.35
#Sta/Elev= 30
  4293.1 1892.95  4359.6 1892.10  4676.8 1891.37  4876.5 1890.04  4919.5 1889.06
  4935.2 1887.27  4941.0 1887.74  4948.7 1886.54  4952.6 1884.98  4953.1 1884.48
  4960.2 1884.48  4960.7 1884.98  4971.8 1886.76  4978.2 1888.38  4984.0 1888.86
  5021.2 1888.56  5036.9 1889.37  5042.7 1889.03  5064.4 1889.92  5074.1 1889.99
  5079.9 1889.53  5101.4 1890.21  5154.5 1889.98  5261.3 1891.17  5429.0 1891.44
  5448.7 1892.07  5492.0 1891.37  5565.5 1891.79  5639.1 1892.42  5661.0 1894.05
#Mann=3,-1,0
  4293.1    0.05       0  4952.6    0.03       0  4960.7    0.05       0
Bank Sta=4952.6,4960.7
Exp/Cntr=0.3,0.1

Chan Stop Cuts=-1