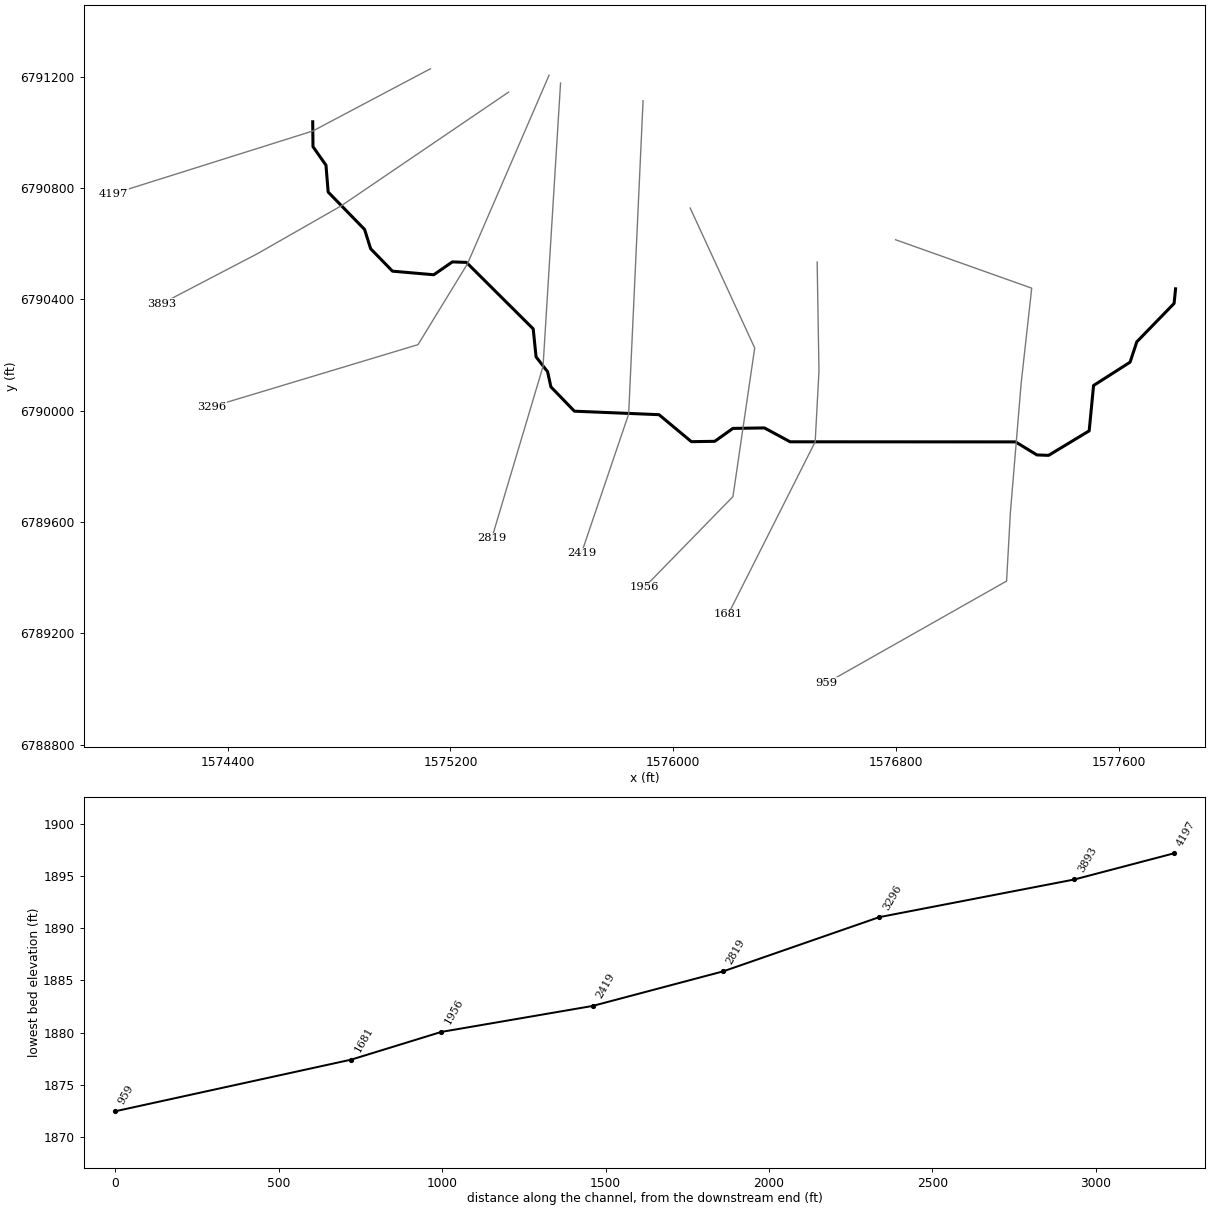
--- Elm 01 76.prj (project) ---

Proj Title=Elm 01 76 Base Level Engineering
Current Plan=p01
Default Exp/Contr=0.3,0.1
English Units
Geom File=g01
Flow File=f01
Plan File=p01
Y Axis Title=Elevation
X Axis Title(PF)=Main Channel Distance
X Axis Title(XS)=Station
BEGIN DESCRIPTION:
Elm 01 76
END DESCRIPTION:
DSS Export Rating Curves= 0
DSS Export Rating Curve Sorted= 0
DSS Export Volume Flow Curves= 0
DXF OffsetX= 0
DXF OffsetY= 0
DXF ScaleX= 1
DXF ScaleY= 10

--- Elm 01 76.p01 (plan) ---

Plan Title=Multiple Run
Short Identifier=Multiple
Geom File=g01
Flow File=f01
Subcritical Flow
K Sum by GR= 0
Std Step Tol= 0.01
Critical Tol= 0.01
Num of Std Step Trials= 20
Max Error Tol= 0.3
Flow Tol Ratio= 0.001
Split Flow NTrial= 30
Split Flow Tol= 0.02
Split Flow Ratio= 0.02
Log Output Level= 0
Friction Slope Method= 1
Unsteady Friction Slope Method= 2
Unsteady Bridges Friction Slope Method= 1
Parabolic Critical Depth
Global Vel Dist=  1 , 1 , 1
Global Log Level= 0
CheckData=True
Encroach Param= -1, 0, 0, 0
BEGIN DESCRIPTION:
Multiple Run
END DESCRIPTION:

--- Elm 01 76.f01 (steady flow) ---

Flow Title=Multiple
Program Version=4.10
Number of Profiles= 7
Profile Names=10-year,25-year,50-year,1pct_min,100-year,1pct_plu,500-year
River Rch & RM=Elm 01 76,Reach-1         ,4197
     240     336     416     320     513     706     790
River Rch & RM=Elm 01 76,Reach-1         ,2819
     336     478     598     464     743    1020    1160
Boundary for River Rch & Prof#=Elm 01 76,Reach-1         , 1
Up Type= 0
Dn Type= 3
Dn Slope=0.006
Boundary for River Rch & Prof#=Elm 01 76,Reach-1         , 2
Up Type= 0
Dn Type= 3
Dn Slope=0.006
Boundary for River Rch & Prof#=Elm 01 76,Reach-1         , 3
Up Type= 0
Dn Type= 3
Dn Slope=0.006
Boundary for River Rch & Prof#=Elm 01 76,Reach-1         , 4
Up Type= 0
Dn Type= 3
Dn Slope=0.006
Boundary for River Rch & Prof#=Elm 01 76,Reach-1         , 5
Up Type= 0
Dn Type= 3
Dn Slope=0.006
Boundary for River Rch & Prof#=Elm 01 76,Reach-1         , 6
Up Type= 0
Dn Type= 3
Dn Slope=0.006
Boundary for River Rch & Prof#=Elm 01 76,Reach-1         , 7
Up Type= 0
Dn Type= 3
Dn Slope=0.006
DSS Import GetInterval= 0
DSS Import GetPeak= 0
DSS Import FillOption= 0

--- Elm 01 76.g01 (geometry) ---

Geom Title=Existing Conditions

River Reach=Elm 01 76,Reach-1
Reach XY= 30
      1574705.00      6791038.00      1574706.02      6790948.42
      1574752.66      6790882.03      1574760.52      6790785.57
      1574891.37      6790651.21      1574913.15      6790581.93
      1574991.66      6790501.36      1575139.78      6790488.52
      1575206.75      6790534.66      1575257.30      6790532.91
      1575497.14      6790294.17      1575507.45      6790193.56
      1575548.86      6790140.17      1575560.82      6790085.69
      1575645.18      6789998.47      1575949.14      6789985.93
      1576065.48      6789888.94      1576149.43      6789890.28
      1576214.67      6789936.63      1576327.83      6789938.31
      1576420.22      6789888.52      1577230.09      6789888.19
      1577306.74      6789841.37      1577348.89      6789839.80
      1577494.65      6789927.88      1577510.37      6790090.70
      1577641.51      6790174.44      1577665.79      6790247.66
      1577799.69      6790385.48      1577805.00      6790438.00

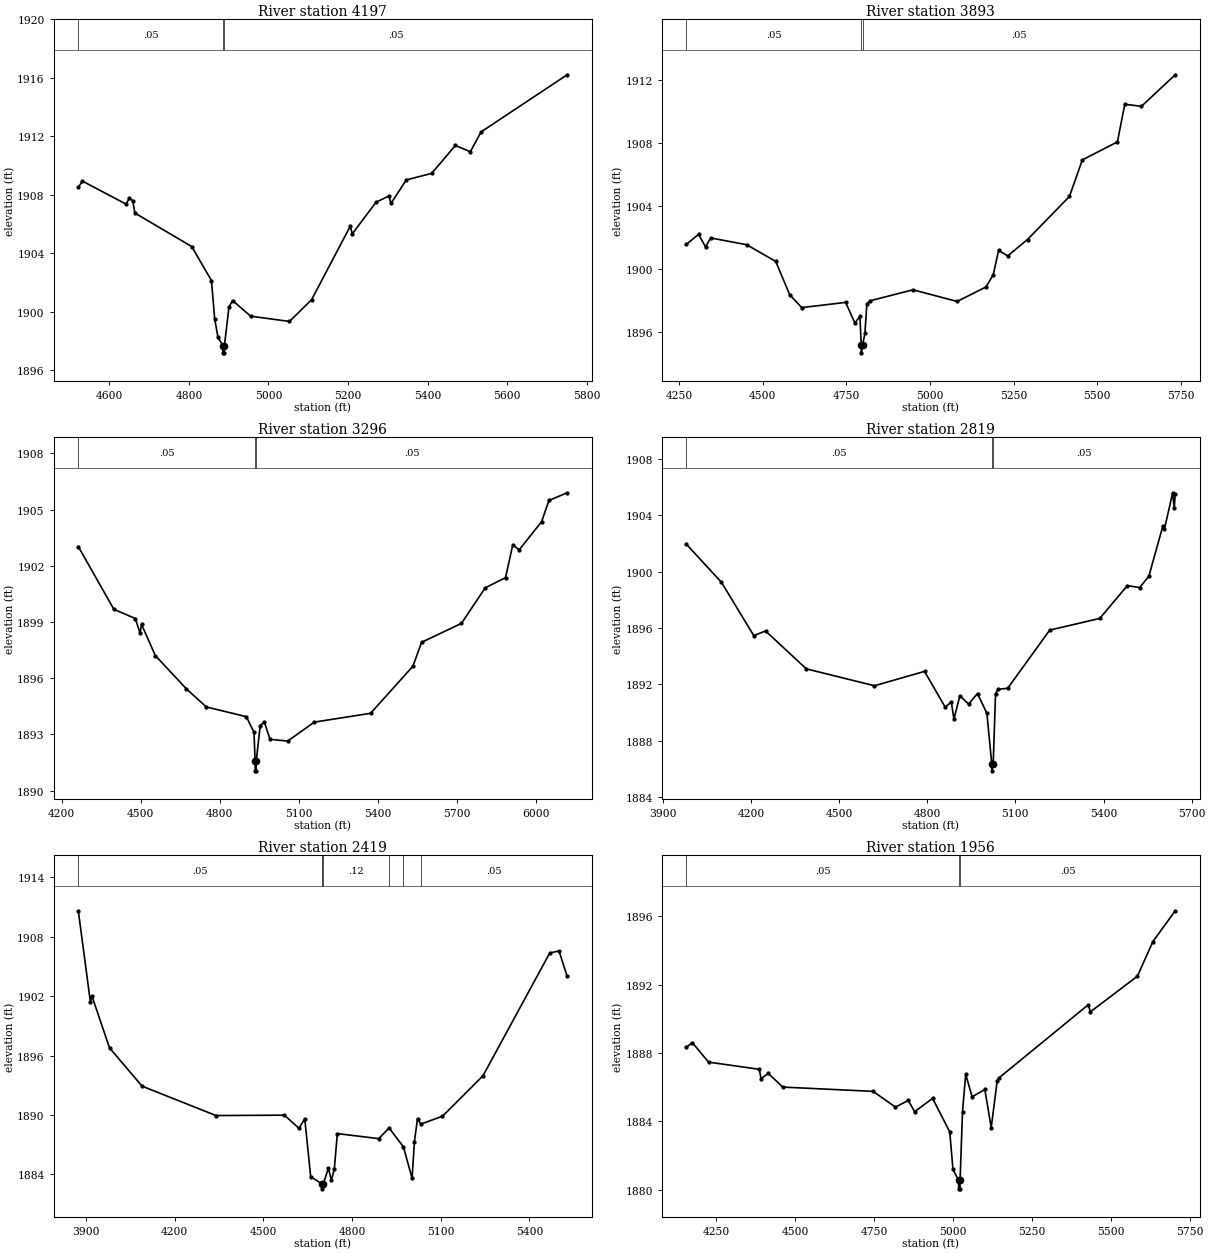
Type RM Length L Ch R = 1,4197,304,304,304
BEGIN DESCRIPTION:
Elm 01 76 3751.145
END DESCRIPTION:
XS GIS Cut Line= 3
      1575127.89      6791228.43      1574705.38      6791004.91
      1573989.33      6790779.46
#Sta/Elev= 30
  4522.0 1908.50  4532.3 1908.93  4642.3 1907.35  4649.7 1907.74  4658.6 1907.60
  4664.3 1906.74  4807.0 1904.45  4856.7 1902.12  4864.7 1899.52  4873.0 1898.23
  4885.3 1897.67  4885.5 1897.17  4889.0 1897.17  4889.3 1897.67  4900.7 1900.31
  4909.9 1900.75  4955.2 1899.68  5052.8 1899.32  5108.4 1900.81  5205.5 1905.84
  5210.7 1905.32  5270.2 1907.48  5302.6 1907.91  5307.8 1907.40  5346.4 1909.01
  5410.2 1909.46  5469.7 1911.37  5507.3 1910.94  5534.5 1912.30  5750.7 1916.21
#Mann=3,-1,0
  4522.0    0.05       0  4885.3    0.03       0  4889.3    0.05       0
Bank Sta=4885.3,4889.3
Exp/Cntr=0.3,0.1

Type RM Length L Ch R = 1,3893,597,597,597
BEGIN DESCRIPTION:
Elm 01 76 3269.622
END DESCRIPTION:
XS GIS Cut Line= 4
      1575408.74      6791144.51      1574806.75      6790735.66
      1574508.18      6790565.11      1574163.12      6790384.98
#Sta/Elev= 30
  4272.3 1901.55  4308.8 1902.19  4329.8 1901.38  4344.7 1901.96  4452.5 1901.53
  4539.3 1900.47  4581.3 1898.35  4617.2 1897.54  4748.3 1897.87  4775.9 1896.56
  4790.9 1896.98  4794.9 1895.17  4795.2 1894.67  4798.9 1895.17  4805.8 1895.90
  4811.8 1897.79  4820.7 1897.97  4949.5 1898.67  5081.4 1897.93  5167.8 1898.85
  5189.4 1899.63  5205.3 1901.17  5232.6 1900.82  5291.7 1901.86  5417.0 1904.59
  5455.5 1906.91  5560.3 1908.05  5582.4 1910.44  5632.2 1910.31  5733.1 1912.31
#Mann=3,-1,0
  4272.3    0.05       0  4794.9    0.03       0  4798.9    0.05       0
Bank Sta=4794.9,4798.9
Exp/Cntr=0.3,0.1

Type RM Length L Ch R = 1,3296,477,477,477
BEGIN DESCRIPTION:
Elm 01 76 3296.16
END DESCRIPTION:
XS GIS Cut Line= 4
      1575554.19      6791205.32      1575261.21      6790528.22
      1575083.26      6790237.42      1574341.09      6790013.90
#Sta/Elev= 30
  4263.3 1903.03  4398.2 1899.68  4479.5 1899.19  4497.6 1898.40  4503.0 1898.88
  4555.4 1897.21  4672.9 1895.44  4748.8 1894.47  4900.6 1893.95  4929.5 1893.12
  4933.9 1891.56  4934.2 1891.06  4937.7 1891.06  4937.9 1891.56  4953.0 1893.46
  4968.6 1893.67  4990.4 1892.74  5057.5 1892.65  5158.1 1893.66  5371.5 1894.13
  5532.0 1896.64  5565.1 1897.92  5716.2 1898.93  5806.5 1900.83  5883.3 1901.37
  5910.8 1903.11  5935.5 1902.86  6020.2 1904.36  6048.0 1905.49  6117.1 1905.90
#Mann=3,-1,0
  4263.3    0.05       0  4933.9    0.05       0  4937.9    0.05       0
Bank Sta=4933.9,4937.9
Exp/Cntr=0.3,0.1

Type RM Length L Ch R = 1,2819,400,400,400
BEGIN DESCRIPTION:
Elm 01 76 2818.69
END DESCRIPTION:
XS GIS Cut Line= 3
      1575595.42      6791177.10      1575532.48      6790159.29
      1575348.35      6789541.92
#Sta/Elev= 30
  3980.1 1901.96  4099.4 1899.26  4209.6 1895.47  4249.7 1895.80  4388.4 1893.11
  4620.4 1891.91  4790.7 1892.93  4860.9 1890.40  4882.0 1890.75  4890.9 1889.54
  4911.0 1891.20  4941.0 1890.61  4971.1 1891.36  5003.1 1889.95  5019.6 1886.37
  5020.0 1885.87  5024.5 1886.37  5032.5 1891.33  5040.6 1891.66  5073.8 1891.73
  5216.8 1895.86  5387.3 1896.69  5481.2 1899.02  5523.0 1898.88  5554.3 1899.68
  5602.3 1903.27  5607.5 1903.04  5635.4 1905.61  5640.7 1904.53  5644.1 1905.51
#Mann=3,-1,0
  3980.1    0.05       0  5019.6    0.05       0  5024.5    0.05       0
Bank Sta=5019.6,5024.5
Exp/Cntr=0.3,0.1

Type RM Length L Ch R = 1,2419,463,463,463
BEGIN DESCRIPTION:
Elm 01 76 2793.594
END DESCRIPTION:
XS GIS Cut Line= 3
      1575891.90      6791113.54      1575840.09      6789988.23
      1575670.54      6789488.51
#Sta/Elev= 30
  3873.5 1910.63  3914.4 1901.43  3919.4 1902.04  3979.1 1896.79  4089.3 1892.92
  4339.5 1889.95  4571.0 1889.99  4619.8 1888.67  4639.8 1889.62  4659.9 1883.77
  4697.2 1883.07  4697.5 1883.05  4697.8 1882.55  4702.4 1883.05  4719.9 1884.64
  4729.9 1883.40  4740.0 1884.59  4750.0 1888.13  4890.1 1887.62  4925.1 1888.70
  4973.7 1886.79  5002.9 1883.61  5010.8 1887.31  5021.4 1889.64  5032.3 1889.09
  5105.8 1889.88  5243.1 1893.98  5468.6 1906.36  5500.0 1906.58  5527.7 1904.01
#Mann=7,-1,0
  3873.5    0.05       0  4697.2    0.12       0  4697.5    0.07       0
  4702.4    0.12       0  4925.1    0.05       0  4973.7    0.12       0
  5032.3    0.05       0
Bank Sta=4697.5,4702.4
Exp/Cntr=0.3,0.1

Type RM Length L Ch R = 1,1956,275,275,275
BEGIN DESCRIPTION:
Mapping XS cca6e87d
END DESCRIPTION:
XS GIS Cut Line= 4
      1576061.17      6790728.13      1576292.94      6790225.51
      1576214.82      6789691.66      1575897.10      6789366.13
#Sta/Elev= 30
  4155.1 1888.34  4174.0 1888.61  4225.4 1887.47  4386.1 1887.05  4391.6 1886.50
  4414.5 1886.81  4460.4 1886.01  4746.5 1885.76  4817.2 1884.84  4857.7 1885.23
  4877.9 1884.57  4934.8 1885.35  4989.1 1883.39  4999.2 1881.20  5016.9 1880.56
  5017.3 1880.06  5021.5 1880.06  5021.8 1880.56  5029.5 1884.58  5039.6 1886.76
  5059.8 1885.44  5100.2 1885.87  5120.4 1883.64  5139.4 1886.39  5144.5 1886.54
  5427.4 1890.82  5434.5 1890.41  5583.0 1892.49  5632.4 1894.52  5703.0 1896.32
#Mann=3,-1,0
  4155.1    0.05       0  5016.9    0.05       0  5021.8    0.05       0
Bank Sta=5016.9,5021.8
Exp/Cntr=0.3,0.1

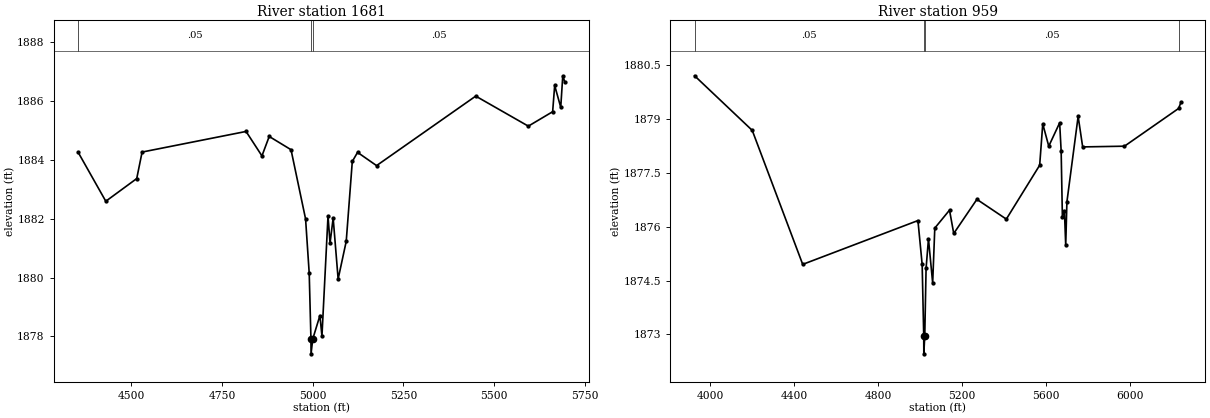
Type RM Length L Ch R = 1,1681,722,722,722
BEGIN DESCRIPTION:
Elm 01 76 2339.049
END DESCRIPTION:
XS GIS Cut Line= 4
      1576517.34      6790534.07      1576523.82      6790141.34
      1576510.20      6789888.49      1576197.46      6789268.50
#Sta/Elev= 30
  4354.0 1884.25  4430.1 1882.59  4515.3 1883.36  4530.1 1884.26  4816.5 1884.96
  4860.3 1884.13  4880.3 1884.79  4940.4 1884.34  4980.5 1881.99  4990.5 1880.15
  4995.3 1877.91  4995.6 1877.41  5000.2 1877.91  5020.0 1878.71  5025.6 1878.01
  5042.3 1882.09  5047.9 1881.17  5056.5 1882.02  5070.2 1879.95  5092.5 1881.23
  5109.2 1883.94  5123.7 1884.25  5176.1 1883.80  5449.3 1886.16  5594.2 1885.14
  5661.2 1885.63  5666.8 1886.52  5683.5 1885.78  5689.1 1886.85  5694.4 1886.65
#Mann=3,-1,0
  4354.0    0.05       0  4995.3    0.05       0  5000.2    0.05       0
Bank Sta=4995.3,5000.2
Exp/Cntr=0.3,0.1

Type RM Length L Ch R = 1,959,0,0,0
BEGIN DESCRIPTION:
Elm 01 76 1878.856
END DESCRIPTION:
XS GIS Cut Line= 6
      1576798.90      6790614.33      1577288.17      6790440.30
      1577250.32      6790099.56      1577211.26      6789630.81
      1577197.89      6789388.21      1576551.33      6789022.30
#Sta/Elev= 30
  3925.2 1880.20  4200.0 1878.68  4440.5 1874.95  4989.6 1876.17  5009.7 1874.95
  5017.2 1872.96  5017.6 1872.46  5022.1 1872.96  5028.4 1874.84  5039.8 1875.66
  5059.8 1874.43  5069.9 1875.96  5140.1 1876.46  5160.2 1875.81  5270.5 1876.76
  5410.8 1876.21  5569.7 1877.71  5584.4 1878.86  5613.0 1878.24  5664.9 1878.89
  5672.1 1878.10  5677.9 1876.28  5687.8 1876.43  5693.8 1875.48  5699.5 1876.69
  5753.0 1879.07  5774.6 1878.22  5973.8 1878.24  6231.6 1879.29  6243.6 1879.47
#Mann=4,-1,0
  3925.2    0.05       0  5017.2    0.03       0  5022.1    0.05       0
  6231.6    0.12       0
Bank Sta=5017.2,5022.1
Exp/Cntr=0.3,0.1

Chan Stop Cuts=-1