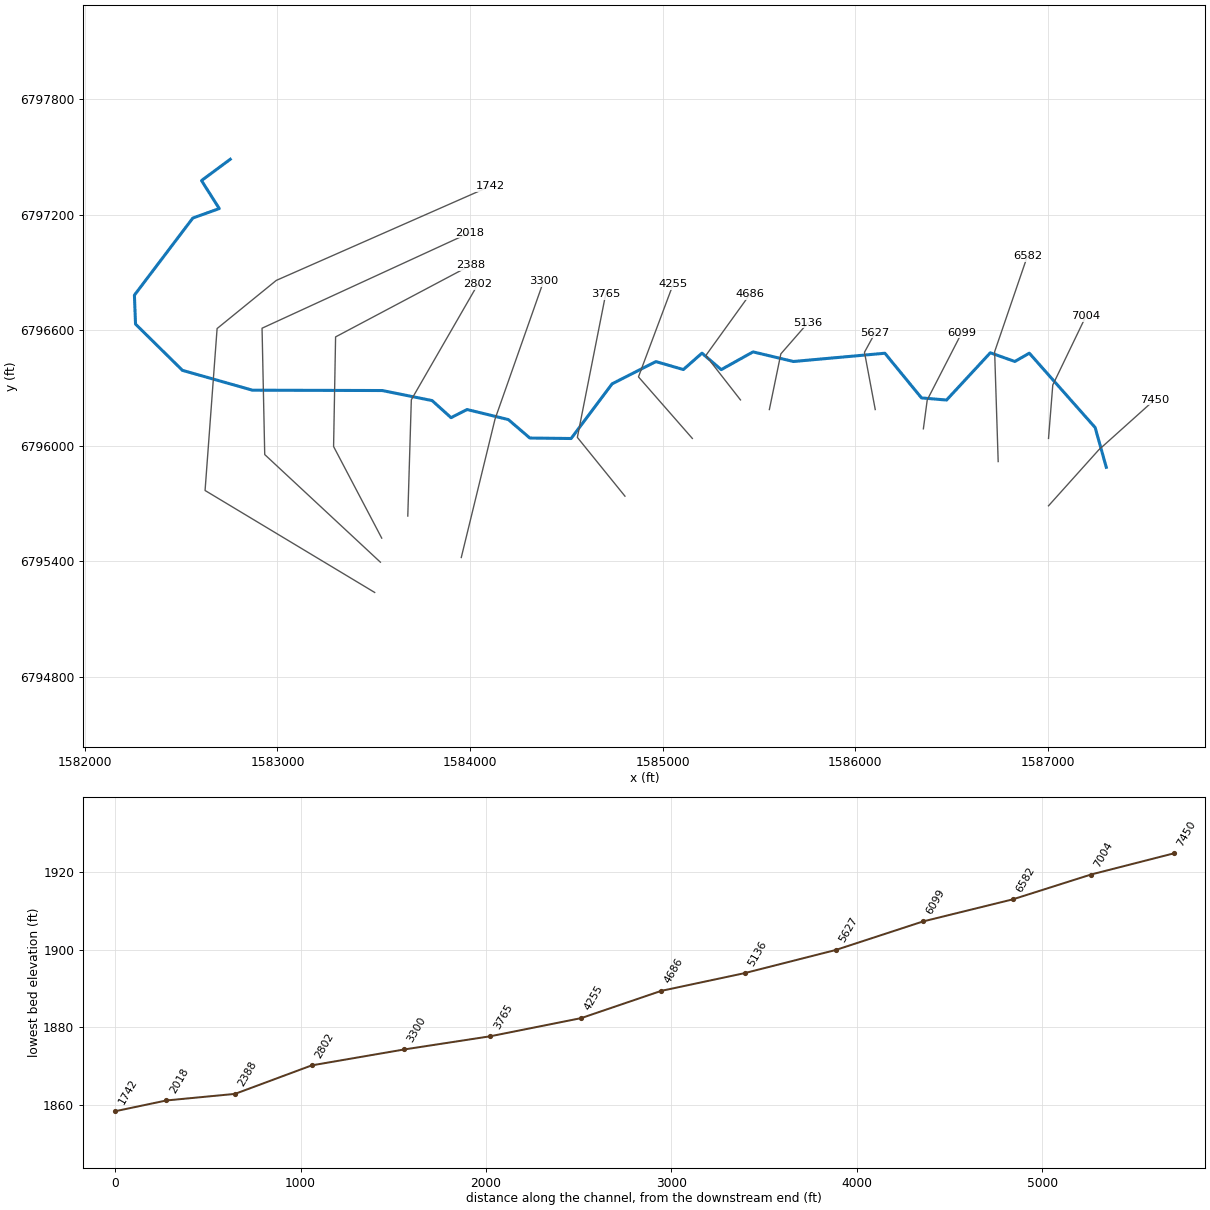
--- Elm 01 77.prj (project) ---

Proj Title=Elm 01 77 Base Level Engineering
Current Plan=p01
Default Exp/Contr=0.3,0.1
English Units
Geom File=g01
Flow File=f01
Plan File=p01
Y Axis Title=Elevation
X Axis Title(PF)=Main Channel Distance
X Axis Title(XS)=Station
BEGIN DESCRIPTION:
Elm 01 77
END DESCRIPTION:
DSS Export Rating Curves= 0
DSS Export Rating Curve Sorted= 0
DSS Export Volume Flow Curves= 0
DXF OffsetX= 0
DXF OffsetY= 0
DXF ScaleX= 1
DXF ScaleY= 10

--- Elm 01 77.p01 (plan) ---

Plan Title=Multiple Run
Short Identifier=Multiple
Geom File=g01
Flow File=f01
Subcritical Flow
K Sum by GR= 0
Std Step Tol= 0.01
Critical Tol= 0.01
Num of Std Step Trials= 20
Max Error Tol= 0.3
Flow Tol Ratio= 0.001
Split Flow NTrial= 30
Split Flow Tol= 0.02
Split Flow Ratio= 0.02
Log Output Level= 0
Friction Slope Method= 1
Unsteady Friction Slope Method= 2
Unsteady Bridges Friction Slope Method= 1
Parabolic Critical Depth
Global Vel Dist=  1 , 1 , 1
Global Log Level= 0
CheckData=True
Encroach Param= -1, 0, 0, 0
BEGIN DESCRIPTION:
Multiple Run
END DESCRIPTION:

--- Elm 01 77.f01 (steady flow) ---

Flow Title=Multiple
Program Version=4.10
Number of Profiles= 7
Profile Names=10-year,25-year,50-year,1pct_min,100-year,1pct_plu,500-year
River Rch & RM=Elm 01 77,Reach-1         ,7450
     206     287     355     273     438     603     674
River Rch & RM=Elm 01 77,Reach-1         ,2802
     414     601     764     602     965    1330    1560
Boundary for River Rch & Prof#=Elm 01 77,Reach-1         , 1
Up Type= 0
Dn Type= 3
Dn Slope=0.01
Boundary for River Rch & Prof#=Elm 01 77,Reach-1         , 2
Up Type= 0
Dn Type= 3
Dn Slope=0.01
Boundary for River Rch & Prof#=Elm 01 77,Reach-1         , 3
Up Type= 0
Dn Type= 3
Dn Slope=0.01
Boundary for River Rch & Prof#=Elm 01 77,Reach-1         , 4
Up Type= 0
Dn Type= 3
Dn Slope=0.01
Boundary for River Rch & Prof#=Elm 01 77,Reach-1         , 5
Up Type= 0
Dn Type= 3
Dn Slope=0.01
Boundary for River Rch & Prof#=Elm 01 77,Reach-1         , 6
Up Type= 0
Dn Type= 3
Dn Slope=0.01
Boundary for River Rch & Prof#=Elm 01 77,Reach-1         , 7
Up Type= 0
Dn Type= 3
Dn Slope=0.01
DSS Import GetInterval= 0
DSS Import GetPeak= 0
DSS Import FillOption= 0

--- Elm 01 77.g01 (geometry) ---

Geom Title=Existing Conditions

River Reach=Elm 01 77,Reach-1
Reach XY= 30
      1587305.00      6795888.00      1587247.21      6796094.44
      1586905.30      6796480.74      1586830.04      6796437.70
      1586702.71      6796482.89      1586475.43      6796237.43
      1586345.18      6796248.46      1586155.02      6796480.46
      1585680.00      6796437.60      1585470.22      6796487.51
      1585304.91      6796395.31      1585205.00      6796480.88
      1585108.42      6796395.83      1584965.49      6796437.05
      1584738.21      6796321.56      1584525.25      6796037.54
      1584310.86      6796040.07      1584199.14      6796135.92
      1583984.79      6796188.21      1583901.60      6796145.83
      1583803.54      6796234.44      1583544.50      6796286.78
      1582870.22      6796288.52      1582506.50      6796391.61
      1582262.81      6796631.81      1582257.05      6796782.14
      1582560.48      6797182.74      1582697.79      6797231.92
      1582605.52      6797377.32      1582755.00      6797488.00

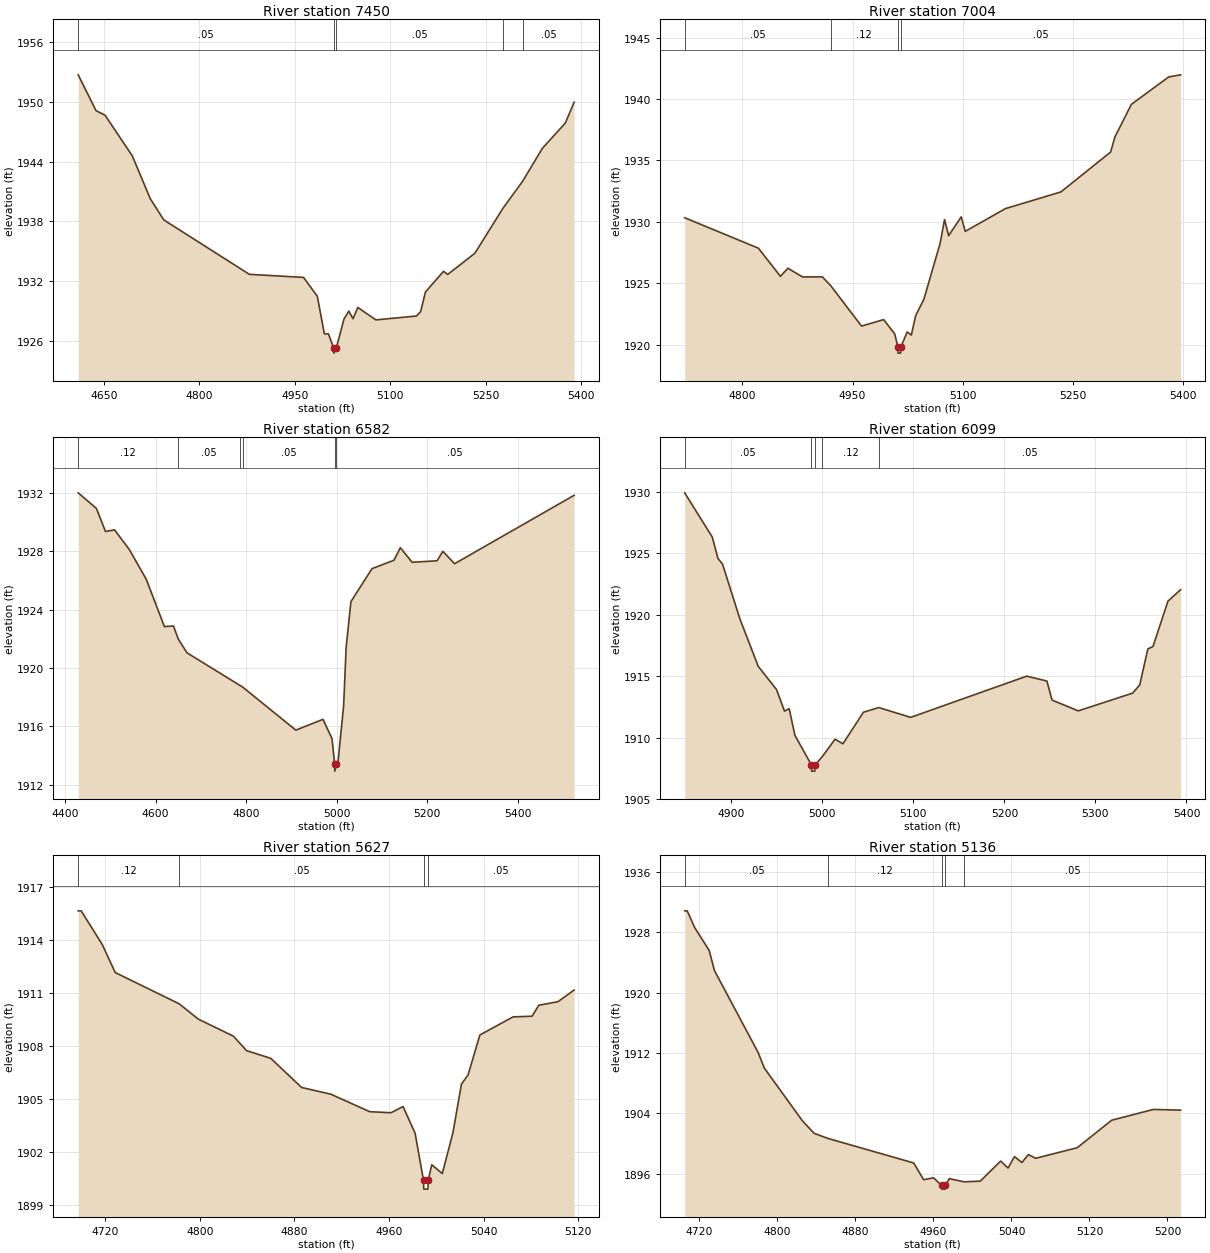
Type RM Length L Ch R = 1,7450,446,446,446
BEGIN DESCRIPTION:
Elm 01 77 7450.434
END DESCRIPTION:
XS GIS Cut Line= 3
      1587004.99      6795687.99      1587265.62      6795978.26
      1587555.03      6796238.03
#Sta/Elev= 30
  4609.9 1952.73  4637.9 1949.13  4652.1 1948.67  4694.8 1944.59  4723.2 1940.27
  4744.3 1938.15  4878.7 1932.68  4963.9 1932.37  4985.5 1930.47  4996.5 1926.70
  5002.9 1926.70  5011.2 1925.26  5011.5 1924.76  5015.2 1925.26  5027.4 1928.19
  5034.9 1928.98  5041.6 1928.22  5049.1 1929.35  5077.5 1928.10  5141.1 1928.49
  5147.8 1928.93  5155.3 1930.90  5183.7 1932.98  5190.4 1932.67  5233.0 1934.80
  5277.0 1939.31  5307.9 1942.03  5339.1 1945.35  5375.0 1947.88  5388.9 1949.98
#Mann=5,-1,0
  4609.9    0.05       0  5011.2    0.05       0  5015.2    0.05       0
  5277.0    0.12       0  5307.9    0.05       0
Bank Sta=5011.2,5015.2
Exp/Cntr=0.3,0.1

Type RM Length L Ch R = 1,7004,422,422,422
BEGIN DESCRIPTION:
Elm 01 77 7004.433
END DESCRIPTION:
XS GIS Cut Line= 3
      1587005.00      6796037.96      1587027.13      6796315.68
      1587199.26      6796672.98
#Sta/Elev= 30
  4721.4 1930.34  4821.8 1927.86  4851.8 1925.57  4861.9 1926.23  4881.9 1925.52
  4908.7 1925.53  4920.1 1924.82  4962.2 1921.52  4992.3 1922.05  5007.4 1920.88
  5011.7 1919.82  5011.9 1919.32  5015.4 1919.32  5015.7 1919.82  5024.4 1921.04
  5030.0 1920.79  5035.9 1922.37  5047.0 1923.69  5069.2 1928.26  5075.2 1930.19
  5080.8 1928.88  5097.9 1930.41  5103.4 1929.23  5158.0 1931.08  5233.6 1932.44
  5301.4 1935.69  5307.0 1936.89  5329.6 1939.57  5380.4 1941.80  5396.6 1941.97
#Mann=4,-1,0
  4721.4    0.05       0  4920.1    0.12       0  5011.7    0.07       0
  5015.7    0.05       0
Bank Sta=5011.7,5015.7
Exp/Cntr=0.3,0.1

Type RM Length L Ch R = 1,6582,483,483,483
BEGIN DESCRIPTION:
Elm 01 77 6581.697
END DESCRIPTION:
XS GIS Cut Line= 3
      1586743.55      6795917.78      1586725.13      6796488.39
      1586895.04      6796984.29
#Sta/Elev= 30
  4429.1 1932.01  4469.3 1930.94  4489.3 1929.36  4509.4 1929.47  4541.8 1928.13
  4579.4 1926.08  4619.4 1922.84  4639.4 1922.88  4650.3 1921.97  4669.4 1921.04
  4785.5 1918.82  4792.0 1918.70  4909.6 1915.74  4969.6 1916.48  4989.6 1915.15
  4995.3 1913.43  4995.6 1912.93  4999.3 1913.43  5002.4 1913.43  5015.2 1917.42
  5020.7 1921.40  5031.3 1924.55  5077.8 1926.81  5126.4 1927.39  5140.4 1928.25
  5166.4 1927.25  5221.6 1927.35  5234.2 1928.00  5260.2 1927.15  5524.2 1931.84
#Mann=6,-1,0
  4429.1    0.12       0  4650.3    0.05       0  4785.5    0.12       0
  4792.0    0.05       0  4995.3    0.05       0  4999.3    0.05       0
Bank Sta=4995.3,4999.3
Exp/Cntr=0.3,0.1

Type RM Length L Ch R = 1,6099,472,472,472
BEGIN DESCRIPTION:
Elm 01 77 6098.621
END DESCRIPTION:
XS GIS Cut Line= 3
      1586354.99      6796087.96      1586375.01      6796237.93
      1586554.98      6796587.97
#Sta/Elev= 30
  4848.7 1929.94  4879.0 1926.34  4885.3 1924.59  4890.3 1924.13  4909.3 1919.68
  4929.5 1915.80  4949.6 1913.91  4958.4 1912.15  4963.5 1912.35  4969.8 1910.18
  4988.0 1907.76  4988.2 1907.26  4991.7 1907.26  4992.0 1907.76  5000.1 1908.46
  5013.9 1909.86  5022.6 1909.49  5045.1 1912.06  5062.0 1912.44  5097.0 1911.64
  5224.5 1915.00  5246.7 1914.60  5252.3 1913.05  5281.2 1912.17  5341.0 1913.62
  5348.7 1914.29  5357.6 1917.22  5363.2 1917.41  5379.7 1921.11  5393.6 1922.05
#Mann=5,-1,0
  4848.7    0.05       0  4988.0    0.05       0  4992.0    0.05       0
  5000.1    0.12       0  5062.0    0.05       0
Bank Sta=4988,4992
Exp/Cntr=0.3,0.1

Type RM Length L Ch R = 1,5627,491,491,491
BEGIN DESCRIPTION:
Elm 01 77 5626.99
END DESCRIPTION:
XS GIS Cut Line= 3
      1586104.99      6796188.04      1586049.11      6796485.64
      1586104.99      6796587.98
#Sta/Elev= 30
  4697.2 1915.64  4699.7 1915.64  4717.5 1913.74  4728.5 1912.15  4782.6 1910.38
  4798.9 1909.51  4828.5 1908.55  4839.6 1907.73  4860.0 1907.30  4886.1 1905.65
  4910.8 1905.27  4943.7 1904.28  4961.7 1904.22  4971.9 1904.57  4982.1 1903.06
  4989.2 1900.40  4989.4 1899.90  4992.9 1899.90  4993.2 1900.40  4996.2 1901.28
  5005.1 1900.78  5014.1 1903.09  5021.3 1905.84  5026.9 1906.36  5036.9 1908.62
  5064.9 1909.64  5081.0 1909.68  5086.7 1910.30  5102.9 1910.50  5116.6 1911.16
#Mann=4,-1,0
  4697.2    0.12       0  4782.6    0.05       0  4989.2    0.05       0
  4993.2    0.05       0
Bank Sta=4989.2,4993.2
Exp/Cntr=0.3,0.1

Type RM Length L Ch R = 1,5136,450,450,450
BEGIN DESCRIPTION:
Elm 01 77 5135.818
END DESCRIPTION:
XS GIS Cut Line= 3
      1585555.00      6796187.99      1585614.67      6796477.09
      1585755.00      6796638.00
#Sta/Elev= 30
  4704.8 1930.87  4707.4 1930.87  4715.0 1928.66  4729.9 1925.62  4735.4 1922.93
  4780.2 1912.06  4786.5 1910.01  4825.4 1903.04  4837.6 1901.35  4851.9 1900.67
  4939.7 1897.42  4949.9 1895.20  4960.1 1895.45  4968.3 1894.45  4968.5 1893.95
  4972.0 1893.95  4972.3 1894.45  4976.2 1895.34  4991.5 1894.92  5008.0 1895.01
  5028.9 1897.67  5036.5 1896.75  5043.1 1898.27  5050.7 1897.48  5057.3 1898.53
  5064.9 1898.04  5107.4 1899.44  5142.8 1903.09  5185.5 1904.52  5213.5 1904.43
#Mann=5,-1,0
  4704.8    0.05       0  4851.9    0.12       0  4968.3    0.05       0
  4972.3    0.12       0  4991.5    0.05       0
Bank Sta=4968.3,4972.3
Exp/Cntr=0.3,0.1

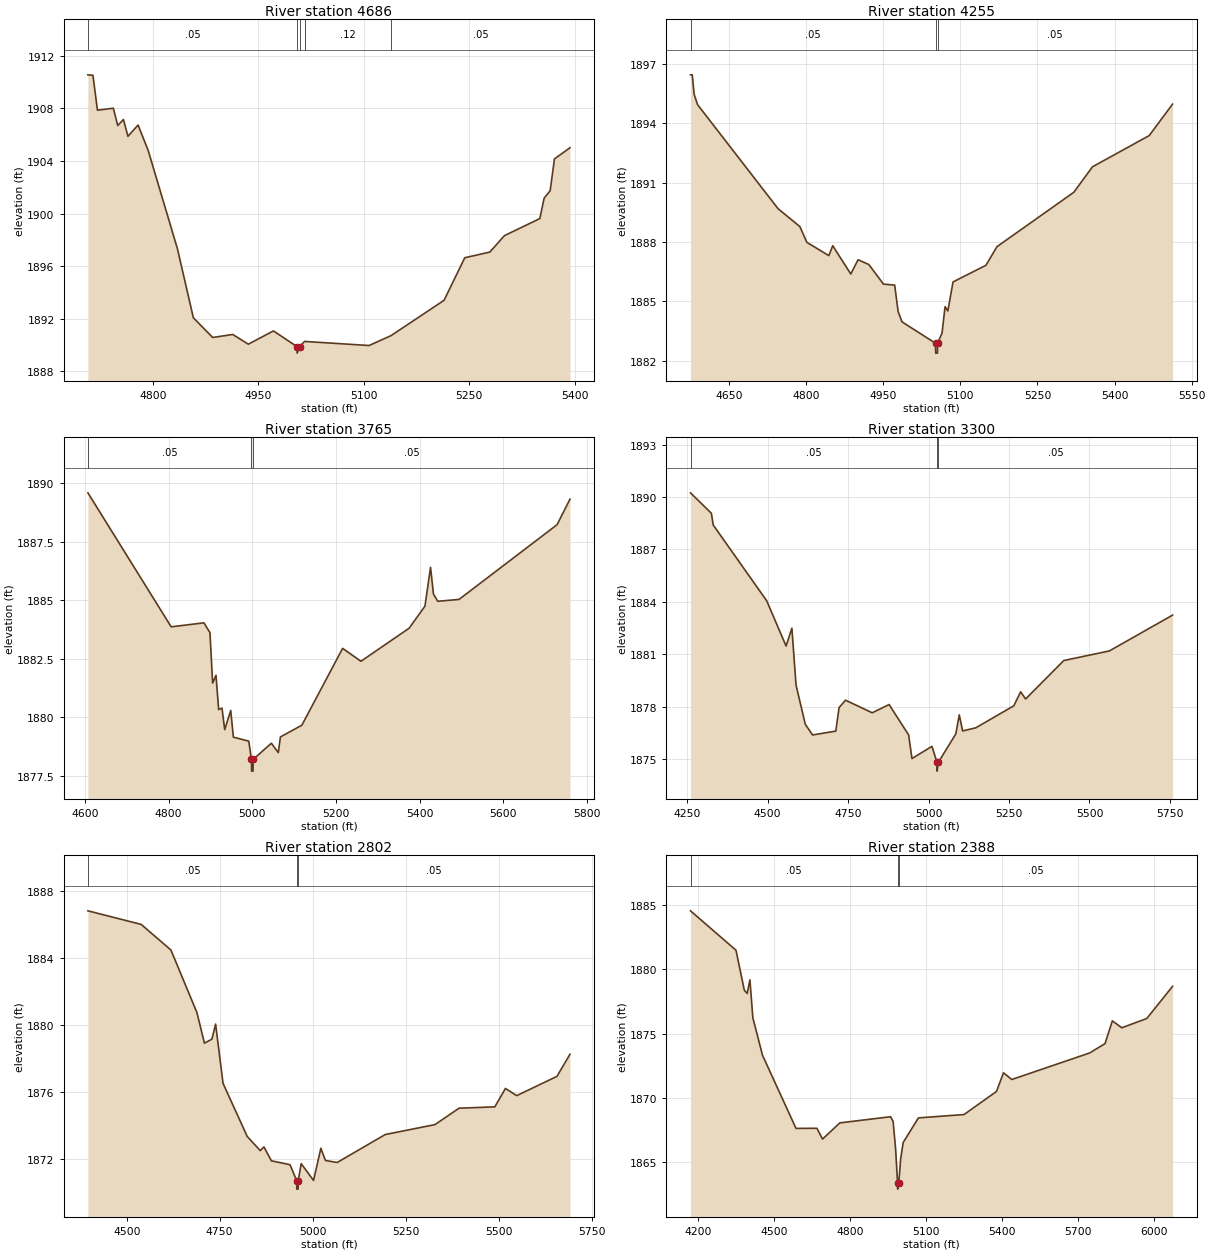
Type RM Length L Ch R = 1,4686,431,431,431
BEGIN DESCRIPTION:
Elm 01 77 4685.943
END DESCRIPTION:
XS GIS Cut Line= 3
      1585404.99      6796238.01      1585225.00      6796468.70
      1585454.99      6796787.99
#Sta/Elev= 30
  4707.4 1910.56  4714.6 1910.52  4721.0 1907.87  4743.6 1908.02  4749.9 1906.70
  4758.0 1907.16  4764.4 1905.88  4778.8 1906.74  4793.3 1904.79  4834.9 1897.31
  4857.5 1892.07  4885.0 1890.57  4913.6 1890.80  4935.7 1890.06  4971.5 1891.07
  5004.9 1889.88  5005.2 1889.38  5008.9 1889.88  5015.7 1890.27  5107.6 1889.96
  5138.8 1890.71  5214.3 1893.40  5243.8 1896.64  5279.4 1897.07  5300.2 1898.32
  5350.6 1899.62  5356.7 1901.17  5365.3 1901.74  5371.4 1904.16  5393.5 1905.01
#Mann=5,-1,0
  4707.4    0.05       0  5004.9    0.03       0  5008.9    0.05       0
  5015.7    0.12       0  5138.8    0.05       0
Bank Sta=5004.9,5008.9
Exp/Cntr=0.3,0.1

Type RM Length L Ch R = 1,4255,490,490,490
BEGIN DESCRIPTION:
Elm 01 77 4254.999
END DESCRIPTION:
XS GIS Cut Line= 3
      1585155.02      6796037.98      1584875.14      6796357.67
      1585055.00      6796838.00
#Sta/Elev= 30
  4575.1 1896.45  4578.5 1896.45  4582.2 1895.46  4588.9 1894.94  4745.5 1889.68
  4787.8 1888.78  4801.5 1887.98  4844.2 1887.31  4851.8 1887.81  4886.9 1886.38
  4901.1 1887.10  4922.0 1886.86  4950.5 1885.87  4972.3 1885.82  4979.0 1884.48
  4986.6 1883.96  5051.7 1882.88  5052.0 1882.38  5055.5 1882.38  5055.7 1882.88
  5064.4 1883.39  5070.3 1884.73  5075.7 1884.51  5085.8 1885.98  5149.8 1886.82
  5171.2 1887.76  5320.7 1890.51  5357.1 1891.80  5467.5 1893.38  5512.9 1894.97
#Mann=3,-1,0
  4575.1    0.05       0  5051.7    0.05       0  5055.7    0.05       0
Bank Sta=5051.7,5055.7
Exp/Cntr=0.3,0.1

Type RM Length L Ch R = 1,3765,465,465,465
BEGIN DESCRIPTION:
Elm 01 77 3765.28
END DESCRIPTION:
XS GIS Cut Line= 3
      1584804.98      6795738.03      1584557.70      6796043.36
      1584705.01      6796788.03
#Sta/Elev= 30
  4607.1 1889.59  4806.1 1883.87  4884.4 1884.04  4898.8 1883.62  4905.2 1881.47
  4913.2 1881.80  4919.6 1880.34  4927.6 1880.40  4934.0 1879.48  4948.4 1880.30
  4954.8 1879.16  4991.5 1878.99  4998.0 1878.21  4998.2 1877.71  5001.7 1877.71
  5002.0 1878.21  5045.5 1878.90  5062.1 1878.50  5067.2 1879.17  5118.4 1879.67
  5215.8 1882.95  5259.6 1882.40  5374.7 1883.81  5412.5 1884.75  5425.9 1886.41
  5432.9 1885.27  5443.1 1884.96  5494.0 1885.04  5728.3 1888.23  5759.1 1889.32
#Mann=3,-1,0
  4607.1    0.05       0  4998.0    0.05       0  5002.0    0.05       0
Bank Sta=4998,5002
Exp/Cntr=0.3,0.1

Type RM Length L Ch R = 1,3300,498,498,498
BEGIN DESCRIPTION:
Elm 01 77 3300.299
END DESCRIPTION:
XS GIS Cut Line= 3
      1583954.74      6795419.48      1584130.04      6796138.11
      1584381.75      6796853.31
#Sta/Elev= 30
  4260.3 1890.24  4325.2 1889.07  4330.8 1888.40  4497.1 1884.06  4557.3 1881.47
  4575.3 1882.49  4588.2 1879.24  4617.0 1876.99  4639.6 1876.38  4711.7 1876.60
  4722.0 1877.95  4742.0 1878.37  4824.9 1877.65  4877.4 1878.12  4938.1 1876.38
  4948.4 1875.03  5010.5 1875.73  5026.2 1874.81  5026.5 1874.31  5030.2 1874.81
  5084.7 1876.44  5095.4 1877.53  5105.9 1876.61  5146.8 1876.79  5264.9 1878.05
  5286.1 1878.85  5301.6 1878.44  5420.1 1880.64  5561.8 1881.19  5758.2 1883.24
#Mann=3,-1,0
  4260.3    0.05       0  5026.2    0.05       0  5030.2    0.05       0
Bank Sta=5026.2,5030.2
Exp/Cntr=0.3,0.1

Type RM Length L Ch R = 1,2802,414,414,414
BEGIN DESCRIPTION:
Elm 01 77 2801.616
END DESCRIPTION:
XS GIS Cut Line= 3
      1583676.97      6795634.80      1583695.34      6796238.82
      1584040.79      6796838.31
#Sta/Elev= 30
  4395.7 1886.83  4539.0 1886.02  4619.0 1884.49  4689.0 1880.75  4709.0 1878.93
  4729.1 1879.17  4739.1 1880.07  4759.1 1876.53  4824.2 1873.36  4859.1 1872.52
  4869.1 1872.74  4889.1 1871.91  4939.1 1871.68  4957.2 1870.72  4957.4 1870.22
  4960.9 1870.22  4961.2 1870.72  4969.2 1871.74  5002.4 1870.74  5022.1 1872.66
  5034.4 1871.93  5066.0 1871.81  5195.3 1873.48  5328.9 1874.07  5393.6 1875.05
  5489.8 1875.13  5518.4 1876.23  5548.7 1875.80  5656.9 1876.95  5691.9 1878.27
#Mann=3,-1,0
  4395.7    0.05       0  4957.2    0.05       0  4961.2    0.05       0
Bank Sta=4957.2,4961.2
Exp/Cntr=0.3,0.1

Type RM Length L Ch R = 1,2388,370,370,370
BEGIN DESCRIPTION:
Elm 01 77 2346.184
END DESCRIPTION:
XS GIS Cut Line= 4
      1583541.57      6795520.17      1583291.55      6795995.88
      1583301.97      6796565.33      1584005.04      6796938.02
#Sta/Elev= 30
  4171.0 1884.56  4350.6 1881.49  4383.2 1878.39  4394.7 1878.12  4405.5 1879.18
  4417.1 1876.23  4455.2 1873.31  4587.5 1867.61  4670.0 1867.62  4692.1 1866.78
  4760.5 1868.04  4960.6 1868.52  4970.6 1868.16  4980.6 1866.01  4988.2 1863.38
  4988.5 1862.88  4993.0 1863.38  5000.6 1865.27  5010.6 1866.52  5070.6 1868.43
  5250.6 1868.69  5378.7 1870.49  5406.3 1871.94  5439.0 1871.42  5746.9 1873.49
  5807.2 1874.22  5836.0 1875.99  5873.2 1875.45  5971.8 1876.17  6073.7 1878.68
#Mann=3,-1,0
  4171.0    0.05       0  4988.2    0.05       0  4993.0    0.05       0
Bank Sta=4988.2,4993
Exp/Cntr=0.3,0.1

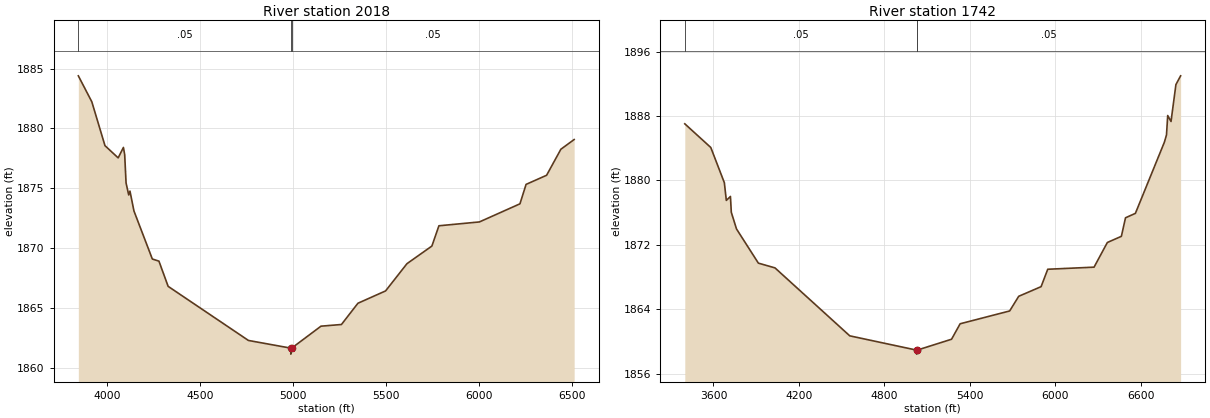
Type RM Length L Ch R = 1,2018,276,276,276
BEGIN DESCRIPTION:
Mapping XS 4eaf47f7
END DESCRIPTION:
XS GIS Cut Line= 4
      1583534.60      6795395.20      1582933.91      6795954.22
      1582920.02      6796610.47      1583999.88      6797106.99
#Sta/Elev= 30
  3845.2 1884.39  3917.6 1882.23  3988.4 1878.57  4059.3 1877.55  4087.6 1878.42
  4094.4 1877.82  4101.8 1875.46  4116.0 1874.46  4122.8 1874.78  4144.3 1873.12
  4243.0 1869.12  4278.6 1868.94  4328.0 1866.84  4759.6 1862.33  4987.2 1861.69
  4987.5 1861.19  4992.1 1861.69  5149.7 1863.52  5259.7 1863.66  5348.2 1865.43
  5497.0 1866.46  5611.9 1868.73  5745.9 1870.20  5783.7 1871.89  6001.5 1872.21
  6219.3 1873.72  6252.2 1875.34  6362.6 1876.10  6439.3 1878.27  6510.7 1879.08
#Mann=3,-1,0
  3845.2    0.05       0  4987.2    0.05       0  4992.1    0.05       0
Bank Sta=4987.2,4992.1
Exp/Cntr=0.3,0.1

Type RM Length L Ch R = 1,1742,0,0,0
BEGIN DESCRIPTION:
Elm 01 77 1874.258
END DESCRIPTION:
XS GIS Cut Line= 5
      1583505.00      6795238.00      1582624.02      6795767.59
      1582686.52      6796608.73      1582993.81      6796858.73
      1584105.79      6797348.32
#Sta/Elev= 30
  3398.9 1887.02  3581.5 1884.08  3676.7 1879.71  3690.6 1877.51  3719.5 1878.00
  3725.6 1876.03  3762.2 1873.96  3915.7 1869.72  4032.3 1869.13  4557.6 1860.69
  5026.4 1858.92  5026.8 1858.42  5031.3 1858.92  5272.5 1860.27  5332.8 1862.19
  5680.6 1863.78  5744.2 1865.60  5901.5 1866.80  5948.2 1868.96  6273.4 1869.22
  6366.7 1872.28  6465.3 1873.05  6494.3 1875.35  6563.7 1875.90  6767.4 1884.74
  6782.2 1885.65  6790.7 1888.05  6814.0 1887.31  6848.3 1891.89  6881.4 1892.98
#Mann=3,-1,0
  3398.9    0.05       0  5026.4    0.05       0  5031.3    0.05       0
Bank Sta=5026.4,5031.3
Exp/Cntr=0.3,0.1

Chan Stop Cuts=-1