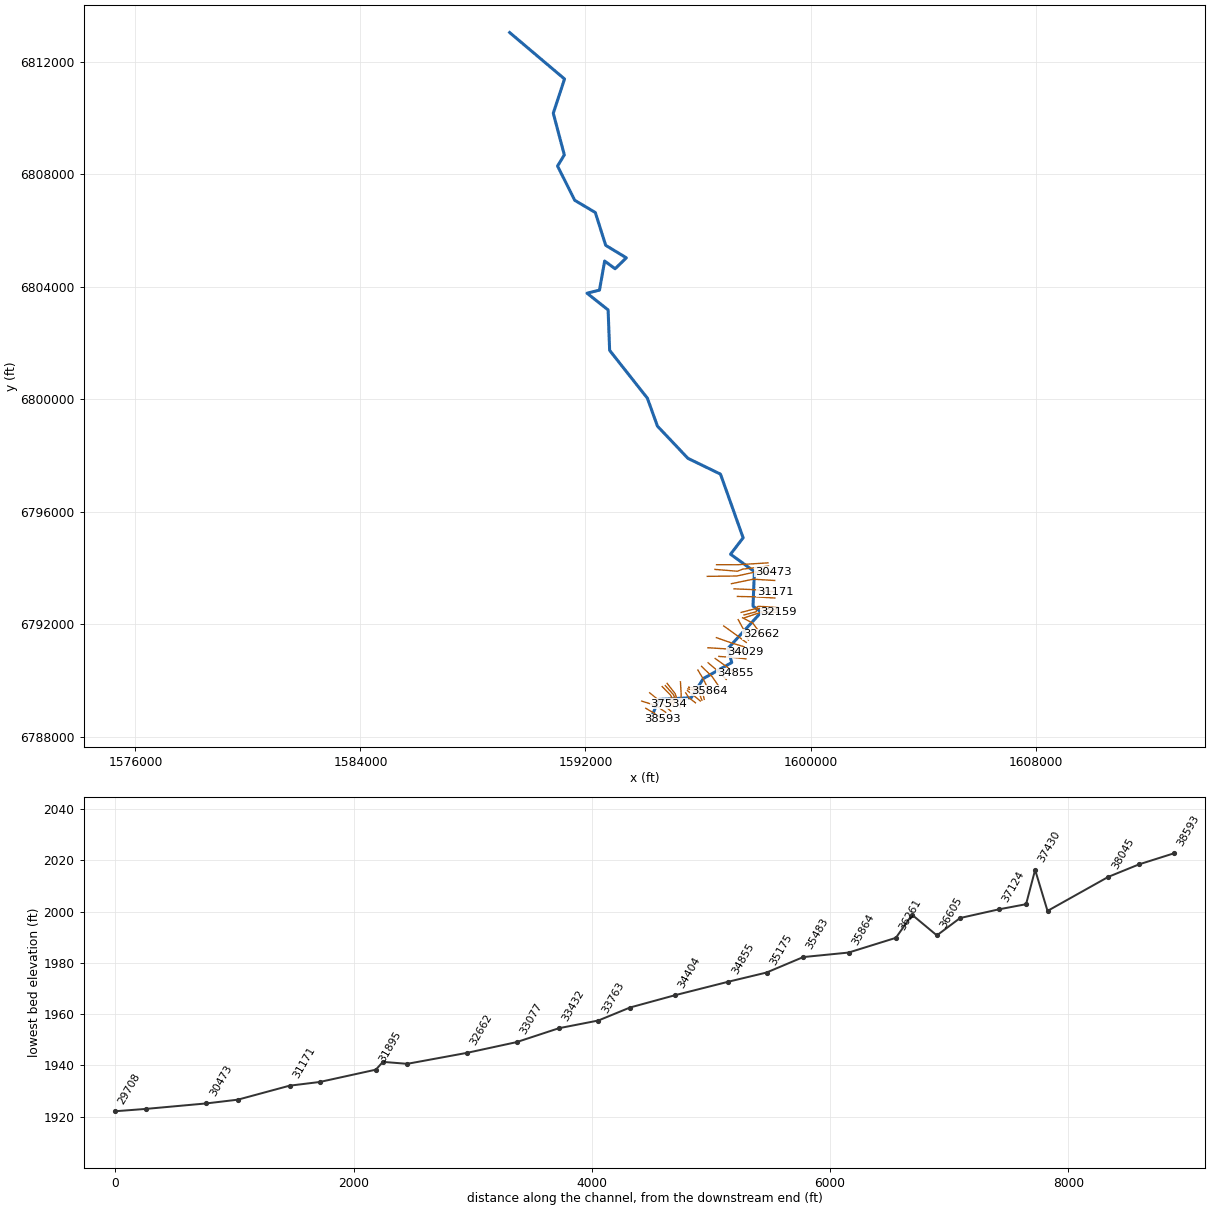
--- Elm 01 78.prj (project) ---

Proj Title=Elm 01 78 Base Level Engineering
Current Plan=p01
Default Exp/Contr=0.3,0.1
English Units
Geom File=g01
Flow File=f01
Plan File=p01
Y Axis Title=Elevation
X Axis Title(PF)=Main Channel Distance
X Axis Title(XS)=Station
BEGIN DESCRIPTION:
Elm 01 78
END DESCRIPTION:
DSS Export Rating Curves= 0
DSS Export Rating Curve Sorted= 0
DSS Export Volume Flow Curves= 0
DXF OffsetX= 0
DXF OffsetY= 0
DXF ScaleX= 1
DXF ScaleY= 10

--- Elm 01 78.p01 (plan) ---

Plan Title=Multiple Run
Short Identifier=Multiple
Geom File=g01
Flow File=f01
Subcritical Flow
K Sum by GR= 0
Std Step Tol= 0.01
Critical Tol= 0.01
Num of Std Step Trials= 20
Max Error Tol= 0.3
Flow Tol Ratio= 0.001
Split Flow NTrial= 30
Split Flow Tol= 0.02
Split Flow Ratio= 0.02
Log Output Level= 0
Friction Slope Method= 1
Unsteady Friction Slope Method= 2
Unsteady Bridges Friction Slope Method= 1
Parabolic Critical Depth
Global Vel Dist=  1 , 1 , 1
Global Log Level= 0
CheckData=True
Encroach Param= -1, 0, 0, 0
BEGIN DESCRIPTION:
Multiple Run
END DESCRIPTION:

--- Elm 01 78.f01 (steady flow) ---

Flow Title=Multiple
Program Version=4.10
Number of Profiles= 7
Profile Names=10-year,25-year,50-year,1pct_min,100-year,1pct_plu,500-year
River Rch & RM=Elm 01 78,Reach-1         ,38593
     278     396     497     387     621     854     982
River Rch & RM=Elm 01 78,Reach-1         ,38045
     401     584     742     586     939    1290    1520
River Rch & RM=Elm 01 78,Reach-1         ,35864
     481     703     897     710    1140    1570    1850
River Rch & RM=Elm 01 78,Reach-1         ,30473
     553     807    1030     810    1300    1790    2100
River Rch & RM=Elm 01 78,Reach-1         ,29708
     553     807    1030     810    1300    1790    2100
River Rch & RM=Elm 01 78,Reach-1         ,19411
     688    1010    1300    1030    1650    2270    2710
River Rch & RM=Elm 01 78,Reach-1         ,17696
     705    1040    1330    1050    1680    2320    2750
River Rch & RM=Elm 01 78,Reach-1         ,16190
     912    1350    1740    1390    2220    3060    3670
River Rch & RM=Elm 01 78,Reach-1         ,12704
     912    1350    1740    1390    2220    3060    3670
River Rch & RM=Elm 01 78,Reach-1         ,8753
     985    1460    1890    1500    2410    3310    3970
River Rch & RM=Elm 01 78,Reach-1         ,5473
    1070    1580    2040    1630    2610    3590    4310
River Rch & RM=Elm 01 78,Reach-1         ,3121
    1070    1580    2040    1630    2610    3590    4310
Boundary for River Rch & Prof#=Elm 01 78,Reach-1         , 1
Up Type= 0
Dn Type= 3
Dn Slope=0.001
Boundary for River Rch & Prof#=Elm 01 78,Reach-1         , 2
Up Type= 0
Dn Type= 3
Dn Slope=0.001
Boundary for River Rch & Prof#=Elm 01 78,Reach-1         , 3
Up Type= 0
Dn Type= 3
Dn Slope=0.001
Boundary for River Rch & Prof#=Elm 01 78,Reach-1         , 4
Up Type= 0
Dn Type= 3
Dn Slope=0.001
Boundary for River Rch & Prof#=Elm 01 78,Reach-1         , 5
Up Type= 0
Dn Type= 3
Dn Slope=0.001
Boundary for River Rch & Prof#=Elm 01 78,Reach-1         , 6
Up Type= 0
Dn Type= 3
Dn Slope=0.001
Boundary for River Rch & Prof#=Elm 01 78,Reach-1         , 7
Up Type= 0
Dn Type= 3
Dn Slope=0.001
DSS Import GetInterval= 0
DSS Import GetPeak= 0
DSS Import FillOption= 0

--- Elm 01 78.g01 (geometry) ---

Geom Title=Existing Conditions

River Reach=Elm 01 78,Reach-1
Reach XY= 30
      1594405.00      6788838.00      1594598.77      6789330.19
      1595757.45      6789393.46      1596187.84      6790071.90
      1597199.75      6790643.44      1597060.07      6791140.29
      1598246.12      6792431.51      1597955.60      6792648.62
      1598004.02      6793877.74      1597156.53      6794493.88
      1597604.11      6795077.42      1596799.17      6797340.30
      1595641.68      6797901.37      1594557.97      6799046.34
      1594199.60      6800040.43      1592858.75      6801739.55
      1592803.80      6803177.50      1592055.54      6803772.46
      1592497.02      6803881.62      1592681.15      6804915.82
      1593053.55      6804641.04      1593452.00      6805030.28
      1592718.37      6805474.27      1592349.55      6806640.47
      1591618.23      6807074.33      1591006.87      6808293.69
      1591247.72      6808688.09      1590854.93      6810169.71
      1591255.00      6811388.00      1589305.00      6813038.00

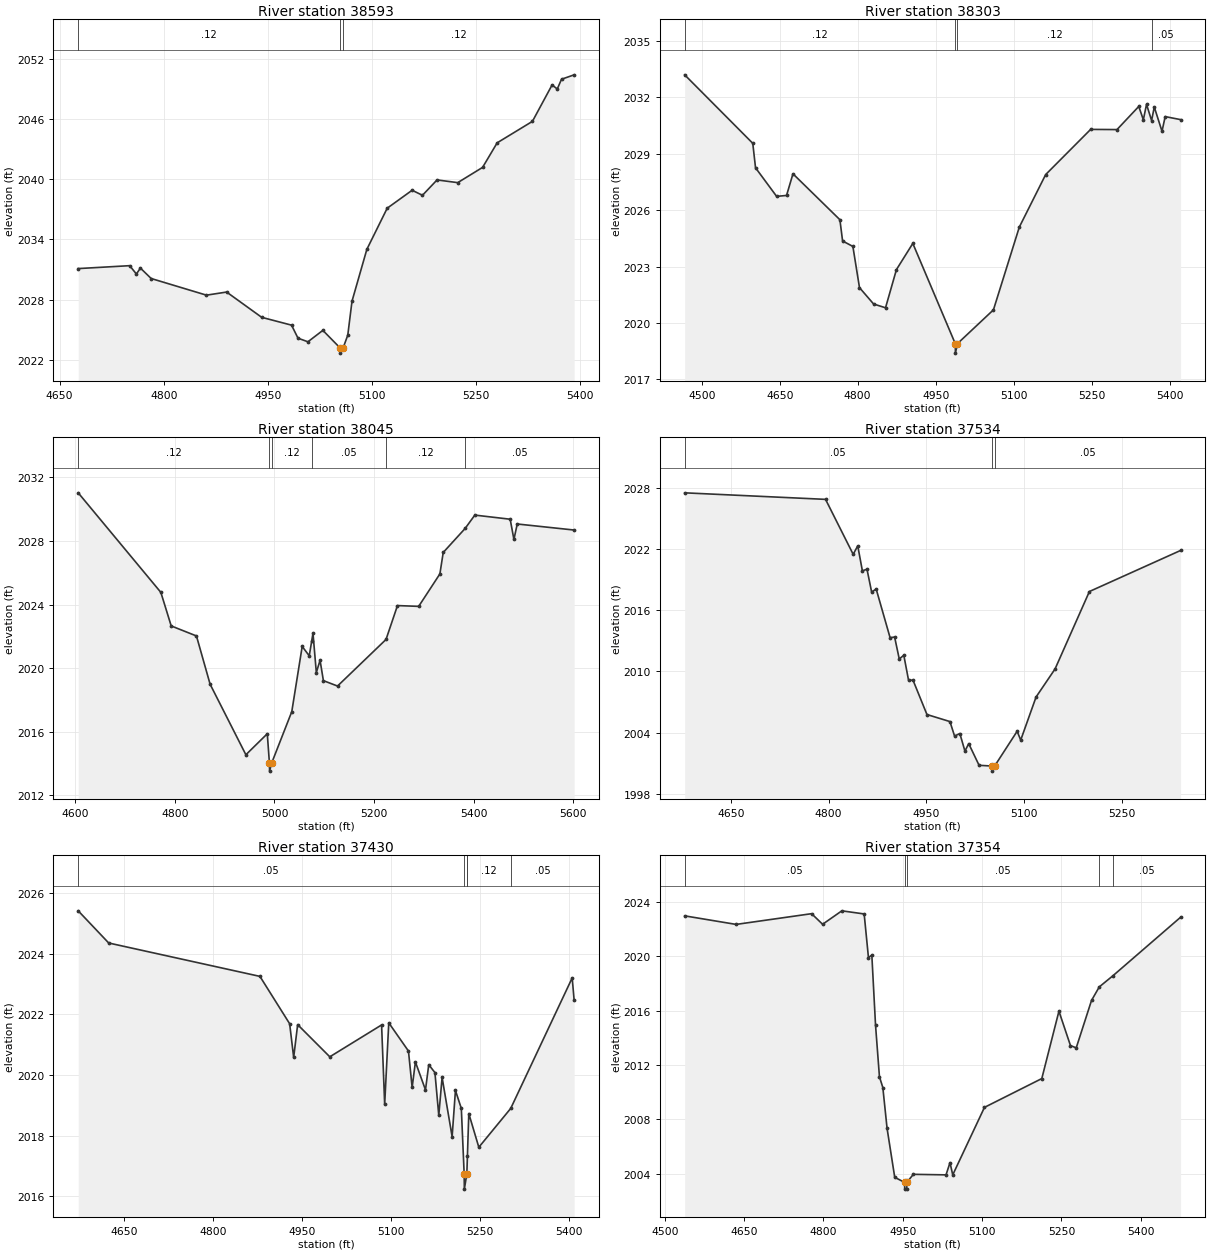
Type RM Length L Ch R = 1,38593,290,290,290
BEGIN DESCRIPTION:
Elm 01 78 38418.69
END DESCRIPTION:
XS GIS Cut Line= 3
      1594142.04      6789018.61      1594418.63      6788851.42
      1594741.18      6788630.06
#Sta/Elev= 30
  4676.8 2031.09  4750.9 2031.38  4760.6 2030.55  4766.4 2031.14  4781.9 2030.10
  4861.5 2028.44  4890.6 2028.75  4941.1 2026.23  4984.1 2025.45  4993.4 2024.15
  5007.7 2023.79  5029.2 2024.93  5054.3 2023.16  5054.5 2022.66  5058.3 2023.16
  5065.1 2024.45  5071.2 2027.84  5092.6 2033.01  5121.9 2037.11  5157.8 2038.90
  5172.7 2038.40  5193.7 2039.93  5223.5 2039.66  5259.3 2041.18  5280.3 2043.63
  5331.1 2045.77  5359.4 2049.40  5366.9 2049.00  5373.0 2049.97  5391.2 2050.41
#Mann=3,-1,0
  4676.8    0.12       0  5054.3    0.07       0  5058.3    0.12       0
Bank Sta=5054.3,5058.3
Exp/Cntr=0.3,0.1

Type RM Length L Ch R = 1,38303,258,258,258
BEGIN DESCRIPTION:
Elm 01 78 38303.33
END DESCRIPTION:
XS GIS Cut Line= 3
      1593996.20      6789272.51      1594504.05      6789113.64
      1594851.32      6788873.92
#Sta/Elev= 30
  4467.2 2033.19  4598.2 2029.55  4603.5 2028.25  4644.1 2026.73  4663.2 2026.78
  4675.5 2027.93  4765.8 2025.49  4771.0 2024.36  4790.8 2024.07  4803.5 2021.88
  4830.7 2021.01  4853.6 2020.81  4874.6 2022.84  4906.1 2024.23  4987.8 2018.90
  4988.1 2018.40  4991.8 2018.90  5061.2 2020.70  5111.0 2025.10  5161.7 2027.89
  5248.2 2030.29  5298.9 2030.28  5340.8 2031.51  5349.6 2030.80  5355.7 2031.62
  5365.5 2030.76  5370.6 2031.48  5385.5 2030.19  5391.6 2030.97  5421.3 2030.81
#Mann=4,-1,0
  4467.2    0.12       0  4987.8    0.07       0  4991.8    0.12       0
  5365.5    0.05       0
Bank Sta=4987.8,4991.8
Exp/Cntr=0.3,0.1

Type RM Length L Ch R = 1,38045,511,511,511
BEGIN DESCRIPTION:
Elm 01 78 38044.83
END DESCRIPTION:
XS GIS Cut Line= 3
      1594281.39      6789568.08      1594586.08      6789318.07
      1595033.98      6788915.74
#Sta/Elev= 30
  4605.8 2031.03  4771.8 2024.77  4792.6 2022.66  4843.3 2022.03  4870.8 2018.99
  4942.6 2014.56  4985.6 2015.88  4989.9 2014.03  4990.2 2013.53  4994.3 2014.03
  5034.8 2017.27  5055.7 2021.37  5069.9 2020.78  5074.7 2021.69  5077.4 2022.20
  5084.1 2019.73  5091.6 2020.50  5098.3 2019.22  5126.7 2018.88  5224.1 2021.81
  5247.1 2023.94  5289.7 2023.89  5332.3 2025.93  5339.0 2027.28  5383.0 2028.79
  5402.5 2029.63  5473.5 2029.37  5481.0 2028.10  5487.7 2029.07  5602.0 2028.69
#Mann=6,-1,0
  4605.8    0.12       0  4989.9    0.07       0  4994.3    0.12       0
  5074.7    0.05       0  5224.1    0.12       0  5383.0    0.05       0
Bank Sta=4989.9,4994.3
Exp/Cntr=0.3,0.1

Type RM Length L Ch R = 1,37534,104,104,104
BEGIN DESCRIPTION:
Elm 01 78 37534.2
END DESCRIPTION:
XS GIS Cut Line= 4
      1594728.12      6789786.82      1595022.39      6789487.34
      1595064.06      6789413.12      1594963.79      6789177.44
#Sta/Elev= 30
  4579.1 2027.48  4795.3 2026.84  4837.7 2021.46  4844.7 2022.29  4851.8 2019.85
  4858.9 2020.00  4866.0 2017.77  4873.0 2018.06  4894.3 2013.31  4901.3 2013.36
  4908.4 2011.22  4915.4 2011.58  4922.6 2009.16  4929.6 2009.13  4950.9 2005.78
  4986.2 2005.09  4993.3 2003.67  5001.4 2003.92  5009.2 2002.20  5015.0 2002.93
  5030.9 2000.81  5050.3 2000.74  5050.7 2000.24  5054.8 2000.74  5089.3 2004.14
  5094.8 2003.28  5118.4 2007.50  5147.5 2010.24  5200.2 2017.82  5340.2 2021.84
#Mann=3,-1,0
  4579.1    0.05       0  5050.3    0.05       0  5054.8    0.05       0
Bank Sta=5050.3,5054.8
Exp/Cntr=0.3,0.1

Type RM Length L Ch R = 1,37430,76,76,76
BEGIN DESCRIPTION:
Elm 01 78 37430.25
END DESCRIPTION:
XS GIS Cut Line= 4
      1594837.48      6789823.30      1595121.35      6789506.87
      1595160.41      6789423.54      1595019.90      6789137.30
#Sta/Elev= 30
  4573.3 2025.41  4624.7 2024.35  4879.6 2023.25  4929.7 2021.69  4936.5 2020.58
  4943.2 2021.66  4997.4 2020.60  5084.7 2021.65  5089.9 2019.03  5096.8 2021.72
  5130.0 2020.79  5136.2 2019.59  5141.7 2020.43  5158.7 2019.51  5164.2 2020.34
  5174.6 2020.08  5181.1 2018.67  5186.7 2019.92  5203.6 2017.97  5209.2 2019.49
  5219.1 2018.90  5223.9 2016.74  5224.2 2016.24  5228.4 2016.74  5229.4 2017.34
  5231.7 2018.73  5248.6 2017.62  5302.4 2018.90  5406.0 2023.20  5409.3 2022.46
#Mann=5,-1,0
  4573.3    0.05       0  5223.9    0.05       0  5228.4    0.05       0
  5229.4    0.12       0  5302.4    0.05       0
Bank Sta=5223.9,5228.4
Exp/Cntr=0.3,0.1

Type RM Length L Ch R = 1,37354,230,230,230
BEGIN DESCRIPTION:
Elm 01 78 37353.86
END DESCRIPTION:
XS GIS Cut Line= 4
      1594901.31      6789901.39      1595187.76      6789538.12
      1595228.12      6789407.91      1595094.01      6789096.72
#Sta/Elev= 30
  4537.5 2022.98  4634.8 2022.35  4777.5 2023.14  4798.3 2022.36  4834.7 2023.35
  4876.9 2023.12  4885.0 2019.91  4891.4 2020.09  4898.4 2014.93  4905.8 2011.13
  4912.2 2010.34  4920.2 2007.34  4934.7 2003.73  4953.2 2003.36  4953.6 2002.86
  4957.4 2002.86  4957.7 2003.36  4969.9 2003.95  5031.7 2003.91  5039.2 2004.81
  5044.4 2003.91  5104.4 2008.88  5212.8 2011.00  5245.2 2015.96  5267.0 2013.43
  5277.9 2013.26  5306.8 2016.75  5321.5 2017.75  5347.6 2018.58  5475.3 2022.88
#Mann=5,-1,0
  4537.5    0.05       0  4953.2    0.05       0  4957.7    0.05       0
  5321.5    0.12       0  5347.6    0.05       0
Bank Sta=4953.2,4957.7
Exp/Cntr=0.3,0.1

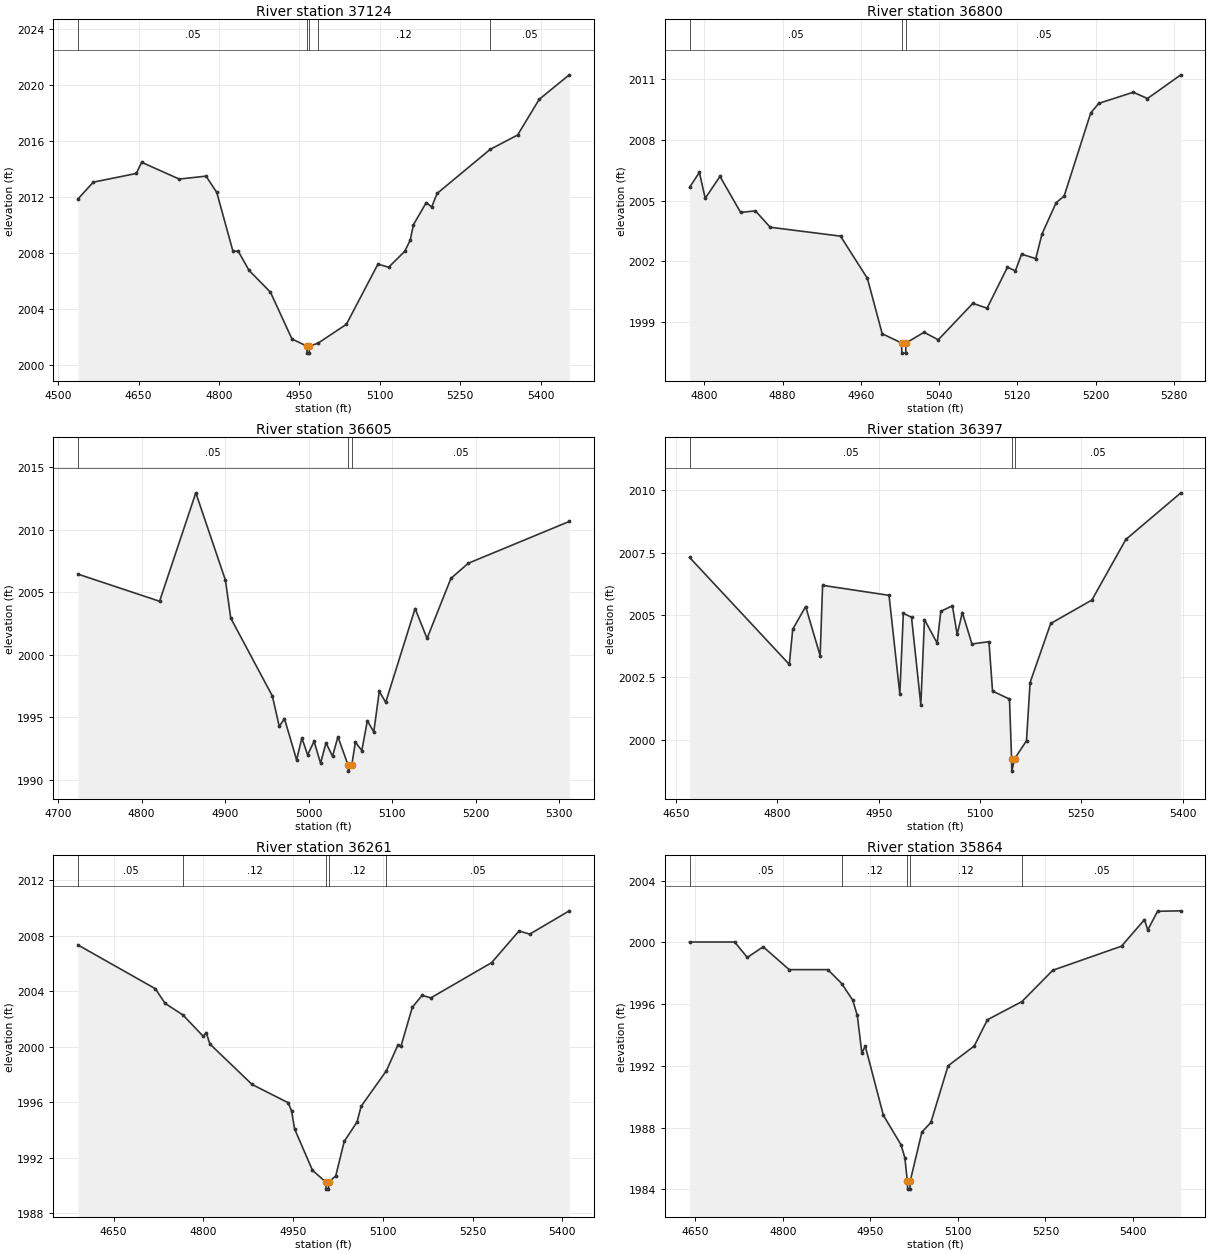
Type RM Length L Ch R = 1,37124,324,324,324
BEGIN DESCRIPTION:
Elm 01 78 37124.44
END DESCRIPTION:
XS GIS Cut Line= 3
      1595375.47      6789956.57      1595402.82      6789496.89
      1595367.73      6789042.03
#Sta/Elev= 30
  4536.9 2011.86  4565.5 2013.06  4645.7 2013.68  4655.7 2014.48  4725.8 2013.28
  4775.9 2013.49  4795.9 2012.32  4826.0 2008.13  4836.0 2008.12  4856.0 2006.76
  4896.1 2005.19  4936.2 2001.85  4964.0 2001.34  4964.3 2000.84  4968.2 2000.84
  4968.5 2001.34  4984.8 2001.55  5037.7 2002.90  5096.6 2007.20  5116.6 2006.98
  5146.7 2008.12  5156.8 2008.91  5162.9 2010.02  5186.8 2011.60  5196.9 2011.28
  5206.9 2012.25  5306.0 2015.40  5357.3 2016.43  5397.5 2018.98  5453.6 2020.73
#Mann=5,-1,0
  4536.9    0.05       0  4964.0    0.07       0  4968.5    0.05       0
  4984.8    0.12       0  5306.0    0.05       0
Bank Sta=4964,4968.5
Exp/Cntr=0.3,0.1

Type RM Length L Ch R = 1,36800,195,195,195
BEGIN DESCRIPTION:
Elm 01 78 36800.47
END DESCRIPTION:
XS GIS Cut Line= 3
      1595561.69      6789567.08      1595677.56      6789390.03
      1595907.99      6789212.97
#Sta/Elev= 30
  4785.0 2005.66  4795.0 2006.40  4801.0 2005.12  4816.1 2006.20  4837.2 2004.42
  4852.3 2004.50  4867.4 2003.69  4939.3 2003.25  4966.8 2001.16  4981.9 1998.43
  5001.7 1997.97  5002.0 1997.47  5005.9 1997.47  5006.2 1997.97  5024.7 1998.50
  5039.2 1998.13  5074.6 1999.93  5089.1 1999.69  5109.9 2001.71  5118.1 2001.54
  5124.4 2002.36  5138.9 2002.14  5145.2 2003.35  5159.7 2004.90  5167.9 2005.23
  5195.1 2009.34  5203.3 2009.81  5238.6 2010.36  5253.1 2010.05  5287.2 2011.22
#Mann=3,-1,0
  4785.0    0.05       0  5001.7    0.05       0  5006.2    0.05       0
Bank Sta=5001.7,5006.2
Exp/Cntr=0.3,0.1

Type RM Length L Ch R = 1,36605,208,208,208
BEGIN DESCRIPTION:
Elm 01 78 36604.6
END DESCRIPTION:
XS GIS Cut Line= 3
      1595622.87      6789642.63      1595842.92      6789474.67
      1596081.14      6789274.00
#Sta/Elev= 30
  4723.9 2006.45  4821.6 2004.28  4865.0 2012.95  4900.5 2005.96  4906.8 2002.94
  4956.7 1996.70  4964.9 1994.28  4971.2 1994.89  4985.7 1991.60  4992.0 1993.35
  4998.9 1992.00  5006.6 1993.08  5014.4 1991.33  5020.9 1992.96  5028.7 1991.89
  5035.2 1993.45  5047.2 1991.20  5047.6 1990.70  5051.8 1991.20  5056.1 1993.02
  5063.8 1992.34  5070.4 1994.73  5078.1 1993.83  5084.7 1997.08  5092.4 1996.20
  5127.6 2003.70  5141.9 2001.31  5170.5 2006.11  5191.3 2007.32  5312.2 2010.66
#Mann=3,-1,0
  4723.9    0.05       0  5047.2    0.05       0  5051.8    0.05       0
Bank Sta=5047.2,5051.8
Exp/Cntr=0.3,0.1

Type RM Length L Ch R = 1,36397,136,136,136
BEGIN DESCRIPTION:
Elm 01 78 36396.81
END DESCRIPTION:
XS GIS Cut Line= 6
      1595637.16      6789705.14      1595825.99      6789663.47
      1595923.65      6789649.15      1595958.81      6789638.73
      1596023.91      6789612.69      1596137.19      6789304.09
#Sta/Elev= 30
  4669.8 2007.31  4817.5 2003.02  4822.6 2004.43  4841.7 2005.34  4863.2 2003.37
  4866.8 2006.19  4965.2 2005.79  4981.2 2001.83  4986.4 2005.07  4998.5 2004.91
  5012.3 2001.40  5017.7 2004.82  5036.5 2003.87  5041.9 2005.15  5059.1 2005.37
  5066.1 2004.22  5073.8 2005.10  5088.0 2003.84  5113.2 2003.93  5118.5 2001.95
  5143.6 2001.63  5146.7 1999.24  5147.0 1998.74  5151.3 1999.24  5168.8 1999.96
  5174.1 2002.29  5204.6 2004.66  5265.6 2005.60  5315.9 2008.03  5397.4 2009.90
#Mann=3,-1,0
  4669.8    0.05       0  5146.7    0.05       0  5151.3    0.05       0
Bank Sta=5146.7,5151.3
Exp/Cntr=0.3,0.1

Type RM Length L Ch R = 1,36261,397,397,397
BEGIN DESCRIPTION:
Elm 01 78 36260.54
END DESCRIPTION:
XS GIS Cut Line= 5
      1595667.13      6789765.03      1595941.88      6789723.37
      1596070.78      6789706.44      1596142.40      6789638.73
      1596221.82      6789334.07
#Sta/Elev= 30
  4590.4 2007.34  4719.7 2004.19  4736.1 2003.13  4765.8 2002.30  4799.8 2000.76
  4804.9 2001.03  4810.8 2000.21  4881.5 1997.29  4942.0 1995.97  4947.5 1995.37
  4952.5 1994.09  4982.4 1991.11  5004.9 1990.25  5005.2 1989.75  5009.1 1989.75
  5009.5 1990.25  5021.3 1990.70  5035.5 1993.19  5056.9 1994.59  5063.8 1995.72
  5106.0 1998.28  5125.2 2000.13  5130.4 2000.05  5149.3 2002.85  5165.7 2003.71
  5180.3 2003.53  5282.0 2006.07  5327.7 2008.35  5345.6 2008.12  5411.7 2009.80
#Mann=5,-1,0
  4590.4    0.05       0  4765.8    0.12       0  5004.9    0.07       0
  5009.5    0.12       0  5106.0    0.05       0
Bank Sta=5004.9,5009.5
Exp/Cntr=0.3,0.1

Type RM Length L Ch R = 1,35864,381,381,381
BEGIN DESCRIPTION:
Elm 01 78 35863.7
END DESCRIPTION:
XS GIS Cut Line= 3
      1595996.91      6790374.20      1596183.52      6790063.90
      1596396.18      6789634.24
#Sta/Elev= 30
  4640.4 2000.02  4717.6 2000.02  4739.3 1999.02  4766.5 1999.71  4811.0 1998.23
  4877.2 1998.23  4901.0 1997.33  4920.0 1996.24  4927.7 1995.26  4935.5 1992.82
  4941.3 1993.28  4972.4 1988.79  5002.5 1986.89  5009.1 1986.05  5013.5 1984.51
  5013.9 1984.01  5017.9 1984.01  5018.2 1984.51  5038.3 1987.70  5053.7 1988.33
  5083.2 1992.00  5128.0 1993.28  5150.5 1994.98  5209.6 1996.16  5262.6 1998.19
  5380.3 1999.75  5419.6 2001.47  5425.2 2000.80  5442.0 2002.01  5481.9 2002.04
#Mann=5,-1,0
  4640.4    0.05       0  4901.0    0.12       0  5013.5    0.07       0
  5018.2    0.12       0  5209.6    0.05       0
Bank Sta=5013.5,5018.2
Exp/Cntr=0.3,0.1

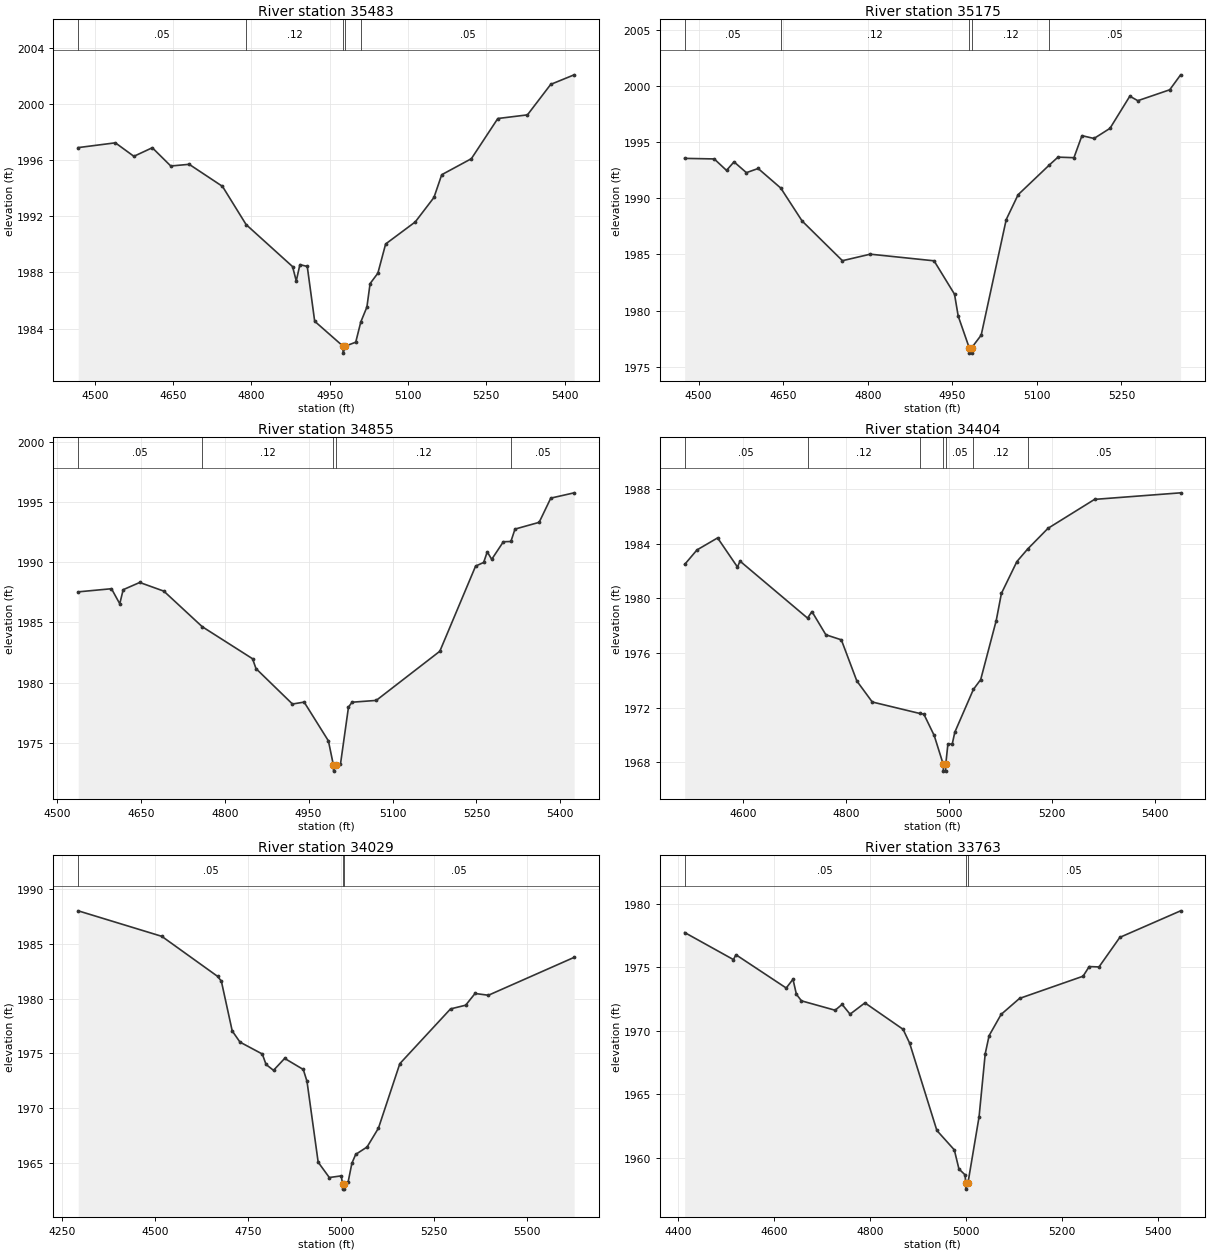
Type RM Length L Ch R = 1,35483,308,308,308
BEGIN DESCRIPTION:
Elm 01 78 35483.48
END DESCRIPTION:
XS GIS Cut Line= 3
      1596124.93      6790508.77      1596502.53      6790142.02
      1596743.26      6789792.86
#Sta/Elev= 30
  4468.0 1996.88  4539.2 1997.22  4574.7 1996.26  4610.0 1996.87  4645.4 1995.57
  4680.7 1995.69  4744.5 1994.12  4789.8 1991.40  4878.8 1988.41  4885.9 1987.39
  4892.9 1988.55  4907.0 1988.42  4921.2 1984.52  4975.4 1982.75  4975.7 1982.25
  4980.2 1982.75  4999.9 1983.03  5009.6 1984.47  5021.3 1985.53  5027.4 1987.20
  5042.3 1987.94  5057.2 1990.02  5114.0 1991.59  5149.8 1993.33  5164.7 1994.95
  5221.5 1996.09  5272.2 1998.95  5329.0 1999.21  5373.6 2001.38  5418.5 2002.06
#Mann=5,-1,0
  4468.0    0.05       0  4789.8    0.12       0  4975.4    0.07       0
  4980.2    0.12       0  5009.6    0.05       0
Bank Sta=4975.4,4980.2
Exp/Cntr=0.3,0.1

Type RM Length L Ch R = 1,35175,320,320,320
BEGIN DESCRIPTION:
Elm 01 78 35174.58
END DESCRIPTION:
XS GIS Cut Line= 3
      1596358.45      6790635.50      1596759.48      6790295.23
      1597004.30      6790040.00
#Sta/Elev= 30
  4475.3 1993.54  4527.7 1993.49  4549.5 1992.47  4562.8 1993.23  4584.8 1992.27
  4605.6 1992.64  4645.7 1990.90  4683.6 1987.97  4755.1 1984.44  4804.5 1985.02
  4917.6 1984.43  4953.9 1981.46  4960.4 1979.52  4979.8 1976.72  4980.2 1976.22
  4984.3 1976.22  4984.6 1976.72  5001.2 1977.82  5045.6 1988.10  5066.7 1990.31
  5121.8 1992.94  5137.4 1993.65  5165.7 1993.60  5179.9 1995.56  5201.3 1995.31
  5229.6 1996.21  5264.8 1999.07  5279.0 1998.67  5335.6 1999.64  5354.9 2000.97
#Mann=5,-1,0
  4475.3    0.05       0  4645.7    0.12       0  4979.8    0.07       0
  4984.6    0.12       0  5121.8    0.05       0
Bank Sta=4979.8,4984.6
Exp/Cntr=0.3,0.1

Type RM Length L Ch R = 1,34855,451,451,451
BEGIN DESCRIPTION:
Elm 01 78 34854.91
END DESCRIPTION:
XS GIS Cut Line= 3
      1596610.18      6790786.55      1596986.91      6790519.19
      1597318.48      6790253.59
#Sta/Elev= 30
  4538.0 1987.53  4597.5 1987.79  4612.3 1986.54  4618.4 1987.71  4648.0 1988.31
  4691.1 1987.59  4759.7 1984.64  4849.7 1981.98  4855.9 1981.16  4921.1 1978.22
  4942.0 1978.38  4985.4 1975.16  4994.3 1973.15  4994.6 1972.65  4999.1 1973.15
  5006.9 1973.21  5021.3 1977.97  5027.7 1978.37  5070.9 1978.52  5184.6 1982.60
  5248.6 1989.67  5263.0 1989.97  5269.4 1990.85  5277.4 1990.23  5298.2 1991.69
  5311.7 1991.71  5319.0 1992.74  5362.2 1993.30  5383.0 1995.31  5424.8 1995.75
#Mann=5,-1,0
  4538.0    0.05       0  4759.7    0.12       0  4994.3    0.07       0
  4999.1    0.12       0  5311.7    0.05       0
Bank Sta=4994.3,4999.1
Exp/Cntr=0.3,0.1

Type RM Length L Ch R = 1,34404,375,375,375
BEGIN DESCRIPTION:
Elm 01 78 34403.57
END DESCRIPTION:
XS GIS Cut Line= 3
      1596741.20      6790860.62      1597253.32      6790823.73
      1597701.32      6790773.96
#Sta/Elev= 30
  4485.8 1982.48  4509.7 1983.54  4549.8 1984.42  4588.4 1982.29  4593.4 1982.72
  4724.7 1978.55  4733.2 1979.03  4760.3 1977.33  4790.4 1976.96  4820.5 1973.95
  4850.5 1972.41  4942.9 1971.57  4950.8 1971.52  4970.9 1969.96  4988.5 1967.85
  4988.8 1967.35  4993.0 1967.35  4993.4 1967.85  4997.6 1969.35  5005.9 1969.32
  5011.0 1970.20  5047.1 1973.33  5061.3 1974.05  5091.5 1978.37  5101.6 1980.36
  5131.7 1982.69  5152.7 1983.61  5192.1 1985.12  5282.7 1987.24  5450.0 1987.72
#Mann=7,-1,0
  4485.8    0.05       0  4724.7    0.12       0  4942.9    0.05       0
  4988.5    0.05       0  4993.4    0.05       0  5047.1    0.12       0
  5152.7    0.05       0
Bank Sta=4988.5,4993.4
Exp/Cntr=0.3,0.1

Type RM Length L Ch R = 1,34029,266,266,266
BEGIN DESCRIPTION:
Elm 01 78 34029.24
END DESCRIPTION:
XS GIS Cut Line= 3
      1596350.55      6791168.79      1597053.66      6791125.38
      1597671.05      6790999.74
#Sta/Elev= 30
  4292.3 1988.01  4517.2 1985.68  4667.5 1982.02  4677.5 1981.58  4706.7 1977.04
  4727.6 1976.02  4787.7 1974.93  4797.7 1973.98  4817.8 1973.44  4847.8 1974.53
  4897.9 1973.52  4907.9 1972.44  4938.0 1965.05  4968.0 1963.65  5000.0 1963.80
  5003.5 1963.09  5003.9 1962.59  5008.1 1962.59  5008.5 1963.09  5018.5 1963.22
  5028.7 1964.95  5038.9 1965.76  5069.6 1966.44  5100.2 1968.16  5157.7 1974.05
  5294.1 1979.05  5334.9 1979.39  5360.1 1980.46  5396.1 1980.30  5626.8 1983.76
#Mann=3,-1,0
  4292.3    0.05       0  5003.5    0.05       0  5008.5    0.05       0
Bank Sta=5003.5,5008.5
Exp/Cntr=0.3,0.1

Type RM Length L Ch R = 1,33763,331,331,331
BEGIN DESCRIPTION:
Elm 01 78 33762.86
END DESCRIPTION:
XS GIS Cut Line= 3
      1596655.10      6791526.84      1597207.13      6791334.15
      1597637.68      6791205.68
#Sta/Elev= 30
  4413.8 1977.73  4515.4 1975.60  4520.7 1975.98  4625.5 1973.36  4639.6 1974.05
  4646.7 1972.87  4657.3 1972.35  4727.5 1971.61  4742.0 1972.07  4758.6 1971.30
  4789.6 1972.19  4869.1 1970.11  4882.8 1969.02  4939.6 1962.14  4976.0 1960.61
  4985.6 1959.11  4998.5 1958.64  4999.5 1958.02  4999.9 1957.52  5004.5 1958.02
  5027.6 1963.22  5040.4 1968.18  5048.5 1969.61  5073.5 1971.28  5111.9 1972.54
  5244.4 1974.29  5257.2 1975.05  5277.6 1975.02  5321.1 1977.35  5447.8 1979.44
#Mann=3,-1,0
  4413.8    0.05       0  4999.5    0.05       0  5004.5    0.05       0
Bank Sta=4999.5,5004.5
Exp/Cntr=0.3,0.1

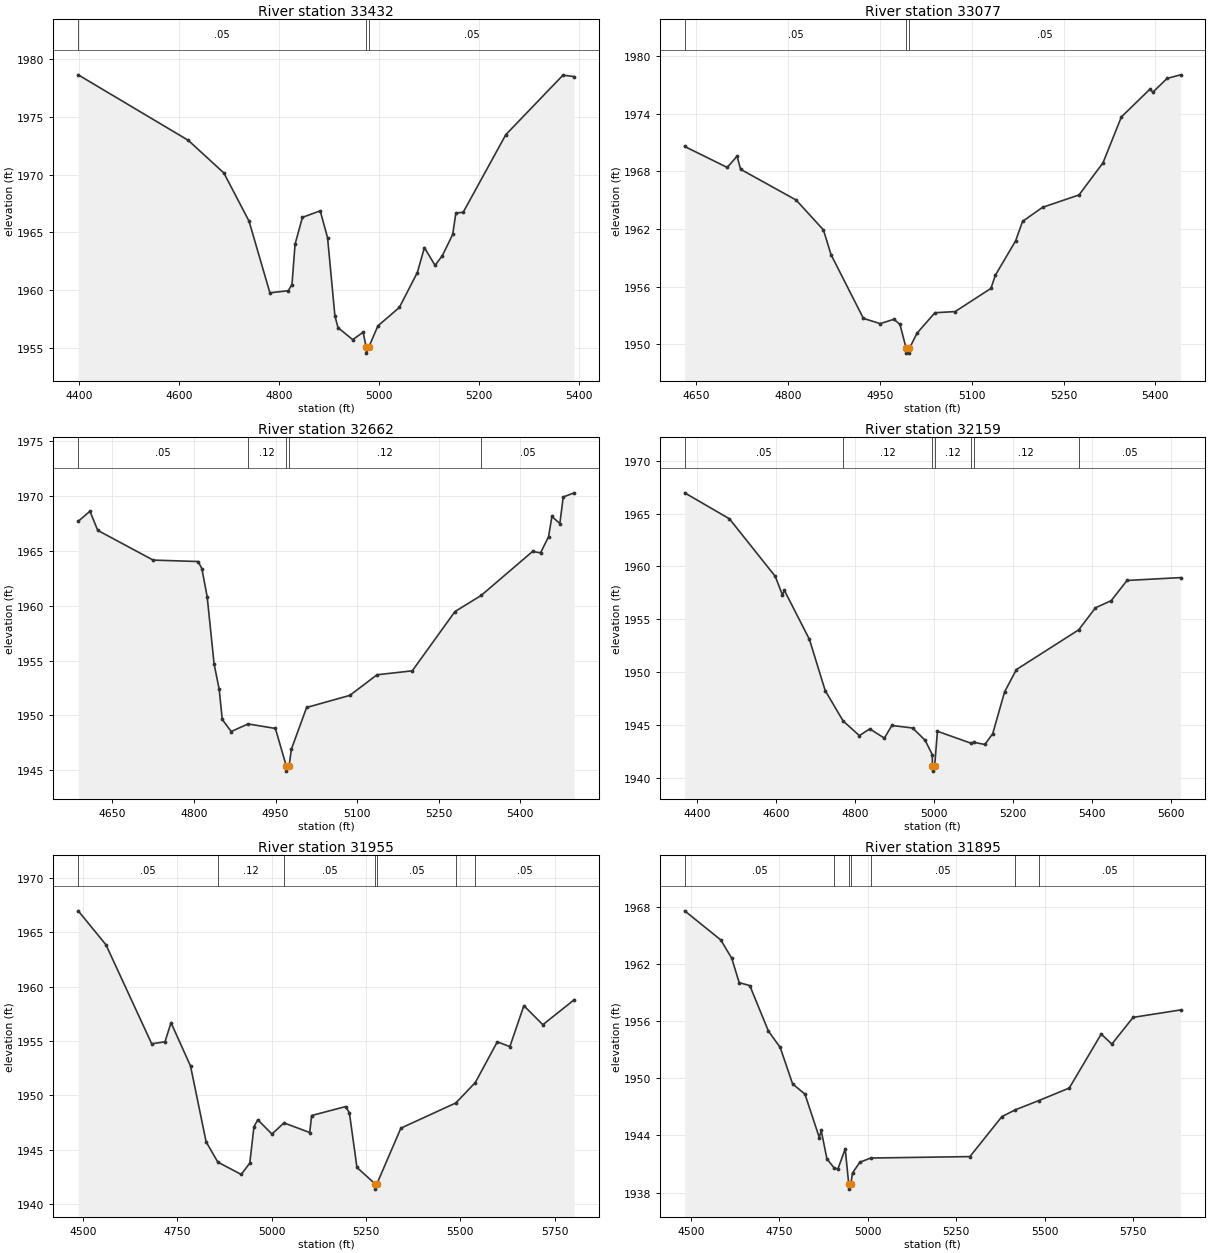
Type RM Length L Ch R = 1,33432,355,355,355
BEGIN DESCRIPTION:
Elm 01 78 33432.4
END DESCRIPTION:
XS GIS Cut Line= 3
      1596913.76      6791943.51      1597401.58      6791592.83
      1597714.12      6791356.69
#Sta/Elev= 30
  4398.8 1978.65  4619.1 1972.97  4690.3 1970.14  4740.7 1965.96  4782.4 1959.75
  4819.1 1959.93  4826.6 1960.47  4832.8 1963.97  4847.5 1966.29  4883.1 1966.86
  4897.8 1964.53  4912.5 1957.76  4918.7 1956.73  4948.1 1955.69  4969.0 1956.33
  4975.1 1955.02  4975.5 1954.52  4980.1 1955.02  4998.5 1956.88  5041.5 1958.48
  5077.5 1961.51  5091.6 1963.67  5112.9 1962.13  5127.5 1962.97  5148.3 1964.82
  5154.6 1966.68  5169.1 1966.72  5254.5 1973.46  5368.9 1978.62  5391.3 1978.50
#Mann=3,-1,0
  4398.8    0.05       0  4975.1    0.05       0  4980.1    0.05       0
Bank Sta=4975.1,4980.1
Exp/Cntr=0.3,0.1

Type RM Length L Ch R = 1,33077,415,415,415
BEGIN DESCRIPTION:
Elm 01 78 33077.19
END DESCRIPTION:
XS GIS Cut Line= 3
      1597428.48      6792167.51      1597606.87      6791843.27
      1597789.00      6791442.59
#Sta/Elev= 30
  4631.1 1970.59  4700.6 1968.41  4716.7 1969.58  4722.4 1968.22  4813.2 1965.02
  4857.8 1961.91  4870.2 1959.34  4923.1 1952.71  4950.6 1952.17  4972.9 1952.62
  4982.8 1952.09  4992.9 1949.60  4993.3 1949.10  4997.9 1949.10  4998.3 1949.60
  5010.6 1951.17  5039.9 1953.30  5072.9 1953.42  5131.4 1955.83  5138.8 1957.22
  5171.7 1960.77  5183.1 1962.80  5215.7 1964.26  5275.3 1965.55  5314.5 1968.89
  5344.5 1973.66  5390.7 1976.52  5396.2 1976.25  5419.2 1977.67  5441.3 1978.04
#Mann=3,-1,0
  4631.1    0.05       0  4992.9    0.05       0  4998.3    0.05       0
Bank Sta=4992.9,4998.3
Exp/Cntr=0.3,0.1

Type RM Length L Ch R = 1,32662,503,503,503
BEGIN DESCRIPTION:
Elm 01 78 32662.36
END DESCRIPTION:
XS GIS Cut Line= 3
      1597583.18      6792234.13      1597947.80      6792044.87
      1598245.46      6791641.65
#Sta/Elev= 30
  4587.0 1967.70  4608.6 1968.61  4622.9 1966.87  4724.8 1964.16  4807.6 1964.03
  4814.4 1963.38  4824.1 1960.84  4836.9 1954.69  4846.2 1952.40  4851.9 1949.64
  4868.4 1948.54  4899.4 1949.23  4949.6 1948.82  4969.4 1945.43  4969.8 1944.93
  4974.9 1945.43  4979.0 1946.93  5007.0 1950.73  5086.4 1951.83  5136.5 1953.71
  5201.3 1954.07  5279.8 1959.47  5328.0 1960.94  5422.6 1964.95  5437.2 1964.82
  5451.9 1966.29  5458.1 1968.14  5472.7 1967.49  5478.9 1969.91  5499.0 1970.29
#Mann=5,-1,0
  4587.0    0.05       0  4899.4    0.12       0  4969.4    0.07       0
  4974.9    0.12       0  5328.0    0.05       0
Bank Sta=4969.4,4974.9
Exp/Cntr=0.3,0.1

Type RM Length L Ch R = 1,32159,204,204,204
BEGIN DESCRIPTION:
Elm 01 78 32158.63
END DESCRIPTION:
XS GIS Cut Line= 3
      1597647.43      6792234.10      1598246.41      6792433.76
      1598870.72      6792430.29
#Sta/Elev= 30
  4368.6 1966.97  4482.0 1964.51  4597.9 1959.07  4615.9 1957.33  4621.2 1957.73
  4684.4 1953.11  4724.4 1948.26  4769.7 1945.39  4810.9 1944.00  4837.3 1944.64
  4874.2 1943.76  4893.1 1944.96  4945.8 1944.72  4977.4 1943.56  4995.4 1942.21
  4996.0 1941.14  4996.4 1940.64  5001.5 1941.14  5008.6 1944.41  5093.6 1943.28
  5100.7 1943.37  5128.6 1943.16  5148.6 1944.19  5178.6 1948.14  5208.6 1950.25
  5366.3 1954.01  5408.6 1956.09  5448.6 1956.77  5488.6 1958.68  5624.3 1958.95
#Mann=7,-1,0
  4368.6    0.05       0  4769.7    0.12       0  4996.0    0.07       0
  5001.5    0.12       0  5093.6    0.05       0  5100.7    0.12       0
  5366.3    0.05       0
Bank Sta=4996,5001.5
Exp/Cntr=0.3,0.1

Type RM Length L Ch R = 1,31955,60,60,60
BEGIN DESCRIPTION:
Elm 01 78 31955.01
END DESCRIPTION:
XS GIS Cut Line= 6
      1597637.02      6792334.80      1598067.59      6792447.65
      1598079.75      6792517.09      1598124.89      6792560.50
      1598248.15      6792569.18      1598857.57      6792504.94
#Sta/Elev= 30
  4487.2 1966.96  4560.8 1963.84  4682.0 1954.75  4717.2 1954.93  4733.2 1956.68
  4784.9 1952.71  4826.3 1945.74  4857.3 1943.88  4919.3 1942.75  4942.0 1943.79
  4953.0 1947.12  4963.1 1947.77  5000.7 1946.46  5032.7 1947.48  5100.9 1946.60
  5105.9 1948.16  5195.9 1948.98  5205.9 1948.43  5226.1 1943.39  5273.5 1941.90
  5274.0 1941.40  5279.1 1941.90  5342.5 1947.00  5488.4 1949.32  5539.8 1951.19
  5598.1 1954.93  5631.4 1954.49  5668.5 1958.25  5718.8 1956.50  5801.8 1958.79
#Mann=7,-1,0
  4487.2    0.05       0  4857.3    0.12       0  5032.7    0.05       0
  5273.5    0.07       0  5279.1    0.05       0  5488.4    0.12       0
  5539.8    0.05       0
Bank Sta=5273.5,5279.1
Exp/Cntr=0.3,0.1

Type RM Length L Ch R = 1,31895,471,471,471
BEGIN DESCRIPTION:
Elm 01 78 31894.89
END DESCRIPTION:
XS GIS Cut Line= 5
      1597536.35      6792425.08      1598038.08      6792557.02
      1598133.57      6792638.62      1598321.07      6792633.41
      1598888.78      6792591.75
#Sta/Elev= 30
  4482.8 1967.62  4584.8 1964.56  4615.8 1962.63  4636.8 1960.07  4666.8 1959.76
  4719.2 1954.99  4752.6 1953.26  4787.8 1949.42  4822.6 1948.35  4863.3 1943.77
  4868.5 1944.54  4884.7 1941.54  4904.9 1940.60  4915.7 1940.48  4936.4 1942.59
  4946.4 1938.86  4946.8 1938.36  4952.0 1938.86  4957.0 1940.06  4977.7 1941.19
  5008.6 1941.63  5288.7 1941.78  5378.9 1945.98  5417.0 1946.70  5483.3 1947.67
  5569.4 1948.99  5659.6 1954.66  5689.7 1953.61  5749.9 1956.42  5884.0 1957.20
#Mann=7,-1,0
  4482.8    0.05       0  4904.9    0.12       0  4946.4    0.07       0
  4952.0    0.12       0  5008.6    0.05       0  5417.0    0.12       0
  5483.3    0.05       0
Bank Sta=4946.4,4952
Exp/Cntr=0.3,0.1

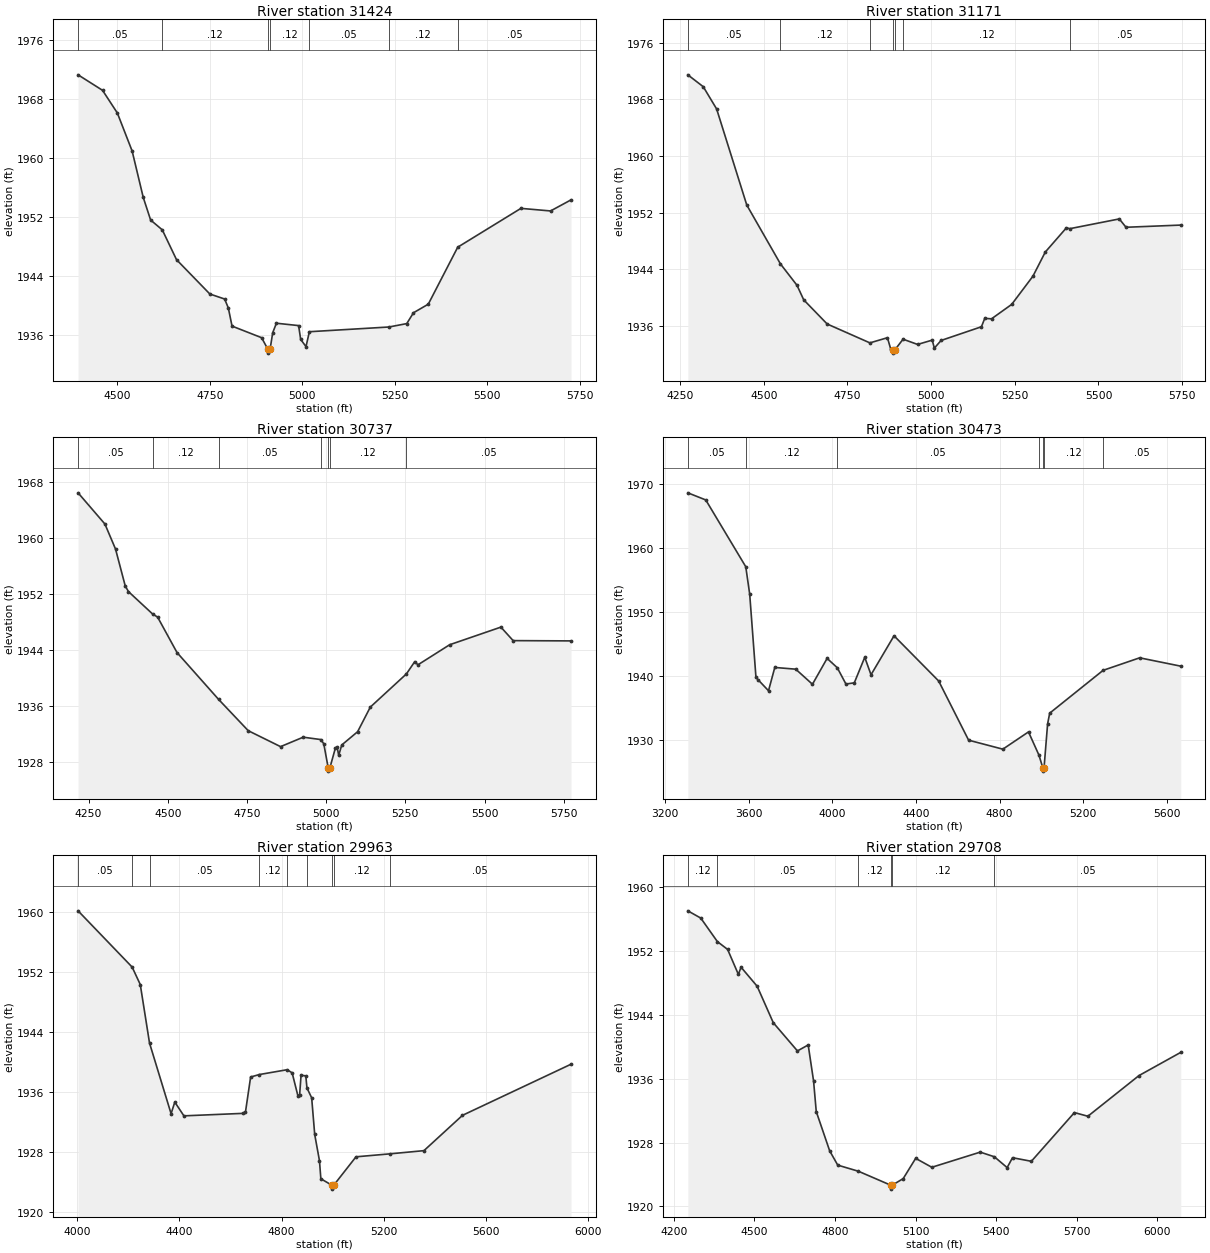
Type RM Length L Ch R = 1,31424,253,253,253
BEGIN DESCRIPTION:
Elm 01 78 31424.14
END DESCRIPTION:
XS GIS Cut Line= 3
      1597398.81      6792991.98      1598001.19      6792979.83
      1598730.19      6792936.43
#Sta/Elev= 30
  4393.5 1971.26  4459.7 1969.16  4499.7 1966.09  4539.7 1960.94  4569.7 1954.66
  4589.7 1951.59  4621.2 1950.26  4659.7 1946.22  4749.8 1941.57  4789.8 1940.89
  4799.8 1939.67  4809.8 1937.22  4889.8 1935.65  4906.9 1934.06  4907.4 1933.56
  4912.6 1934.06  4919.8 1936.33  4929.8 1937.61  4989.8 1937.29  4995.4 1935.42
  5009.8 1934.44  5018.9 1936.46  5234.1 1937.10  5282.2 1937.56  5300.4 1939.03
  5340.4 1940.19  5420.0 1947.91  5590.9 1953.17  5671.0 1952.82  5726.3 1954.32
#Mann=7,-1,0
  4393.5    0.05       0  4621.2    0.12       0  4906.9    0.07       0
  4912.6    0.12       0  5018.9    0.05       0  5234.1    0.12       0
  5420.0    0.05       0
Bank Sta=4906.9,4912.6
Exp/Cntr=0.3,0.1

Type RM Length L Ch R = 1,31171,434,434,434
BEGIN DESCRIPTION:
Elm 01 78 31170.51
END DESCRIPTION:
XS GIS Cut Line= 3
      1597278.98      6793262.81      1598004.66      6793233.30
      1598747.74      6793158.64
#Sta/Elev= 30
  4272.9 1971.48  4319.0 1969.80  4359.0 1966.65  4449.1 1953.06  4549.7 1944.74
  4599.2 1941.71  4619.2 1939.66  4689.3 1936.24  4817.0 1933.57  4869.4 1934.30
  4879.4 1932.67  4886.6 1932.62  4887.0 1932.12  4892.3 1932.62  4916.1 1934.09
  4959.5 1933.35  5003.3 1933.96  5009.6 1932.83  5029.7 1933.91  5150.3 1935.85
  5160.3 1937.04  5180.4 1936.97  5240.7 1939.01  5304.2 1943.00  5341.2 1946.42
  5404.4 1949.85  5414.4 1949.72  5562.3 1951.10  5582.4 1949.92  5746.0 1950.23
#Mann=7,-1,0
  4272.9    0.05       0  4549.7    0.12       0  4817.0    0.05       0
  4886.6    0.07       0  4892.3    0.05       0  4916.1    0.12       0
  5414.4    0.05       0
Bank Sta=4886.6,4892.3
Exp/Cntr=0.3,0.1

Type RM Length L Ch R = 1,30737,264,264,264
BEGIN DESCRIPTION:
Elm 01 78 30737.31
END DESCRIPTION:
XS GIS Cut Line= 3
      1597189.17      6793445.27      1597956.57      6793605.00
      1598727.40      6793559.86
#Sta/Elev= 30
  4216.9 1966.44  4301.7 1961.98  4335.2 1958.40  4365.9 1953.12  4376.1 1952.32
  4452.3 1949.12  4468.0 1948.68  4529.3 1943.61  4660.3 1936.93  4754.0 1932.45
  4856.1 1930.17  4927.6 1931.52  4983.2 1931.18  4992.5 1930.58  5006.3 1927.17
  5006.8 1926.67  5012.0 1927.17  5029.2 1929.98  5034.6 1930.13  5039.6 1928.93
  5049.3 1930.41  5099.3 1932.30  5139.4 1935.82  5253.3 1940.56  5279.7 1942.32
  5289.7 1941.86  5389.8 1944.73  5551.6 1947.25  5590.2 1945.32  5772.9 1945.28
#Mann=7,-1,0
  4216.9    0.05       0  4452.3    0.12       0  4660.3    0.05       0
  4983.2    0.12       0  5006.3    0.07       0  5012.0    0.12       0
  5253.3    0.05       0
Bank Sta=5006.3,5012
Exp/Cntr=0.3,0.1

Type RM Length L Ch R = 1,30473,510,510,510
BEGIN DESCRIPTION:
Elm 01 78 30472.64
END DESCRIPTION:
XS GIS Cut Line= 4
      1596329.18      6793706.21      1597374.84      6793718.49
      1598006.66      6793853.78      1598671.42      6793868.94
#Sta/Elev= 30
  3309.4 1968.56  3395.2 1967.45  3586.4 1957.05  3605.2 1952.79  3635.2 1939.81
  3645.2 1939.45  3695.2 1937.73  3725.2 1941.36  3825.3 1941.09  3905.3 1938.74
  3975.3 1942.77  4023.9 1941.32  4065.3 1938.78  4105.3 1938.96  4155.3 1942.94
  4185.3 1940.22  4295.3 1946.29  4508.7 1939.25  4651.9 1930.03  4815.5 1928.63
  4938.2 1931.32  4988.3 1927.69  5006.8 1925.71  5007.2 1925.21  5012.5 1925.71
  5029.6 1932.59  5039.6 1934.24  5294.9 1940.91  5469.7 1942.86  5666.2 1941.56
#Mann=7,-1,0
  3309.4    0.05       0  3586.4    0.12       0  4023.9    0.05       0
  4988.3    0.12       0  5006.8    0.07       0  5012.5    0.12       0
  5294.9    0.05       0
Bank Sta=5006.8,5012.5
Exp/Cntr=0.3,0.1

Type RM Length L Ch R = 1,29963,255,255,255
BEGIN DESCRIPTION:
Elm 01 78 29962.97
END DESCRIPTION:
XS GIS Cut Line= 4
      1596602.62      6793953.61      1597403.36      6793888.51
      1597583.48      6793962.29      1598505.83      6794072.97
#Sta/Elev= 30
  4004.7 1960.09  4216.2 1952.60  4247.9 1950.28  4284.1 1942.49  4368.3 1933.10
  4382.9 1934.64  4418.4 1932.81  4649.2 1933.14  4659.2 1933.34  4679.3 1937.98
  4713.8 1938.31  4822.2 1938.95  4841.6 1938.53  4863.9 1935.50  4871.0 1935.65
  4876.4 1938.21  4895.0 1938.13  4899.4 1936.53  4917.9 1935.21  4929.8 1930.33
  4948.4 1926.84  4953.8 1924.44  4997.9 1923.56  4998.4 1923.06  5003.7 1923.56
  5091.2 1927.36  5222.5 1927.75  5356.8 1928.18  5507.5 1932.88  5931.7 1939.68
#Mann=9,-1,0
  4004.7    0.05       0  4216.2    0.12       0  4284.1    0.05       0
  4713.8    0.12       0  4822.2    0.05       0  4899.4    0.12       0
  4997.9    0.07       0  5003.7    0.12       0  5222.5    0.05       0
Bank Sta=4997.9,5003.7
Exp/Cntr=0.3,0.1

Type RM Length L Ch R = 1,29708,482,482,482
BEGIN DESCRIPTION:
Elm 01 78 29870.88
END DESCRIPTION:
XS GIS Cut Line= 3
      1596656.80      6794120.71      1597404.90      6794119.81
      1598490.30      6794185.80
#Sta/Elev= 30
  4251.9 1957.06  4300.1 1956.15  4362.0 1953.20  4400.1 1952.22  4440.1 1949.09
  4450.1 1949.99  4510.1 1947.60  4570.1 1943.03  4660.1 1939.49  4700.1 1940.24
  4720.1 1935.73  4730.1 1931.89  4780.1 1926.96  4810.1 1925.17  4887.3 1924.40
  5007.0 1922.66  5007.5 1922.16  5013.2 1922.66  5053.9 1923.48  5100.3 1926.02
  5160.4 1924.90  5340.7 1926.80  5393.2 1926.22  5440.9 1924.86  5460.9 1926.10
  5531.1 1925.65  5691.4 1931.76  5741.5 1931.30  5931.8 1936.40  6087.4 1939.31
#Mann=6,-1,0
  4251.9    0.12       0  4362.0    0.05       0  4887.3    0.12       0
  5007.0    0.07       0  5013.2    0.12       0  5393.2    0.05       0
Bank Sta=5007,5013.2
Exp/Cntr=0.3,0.1