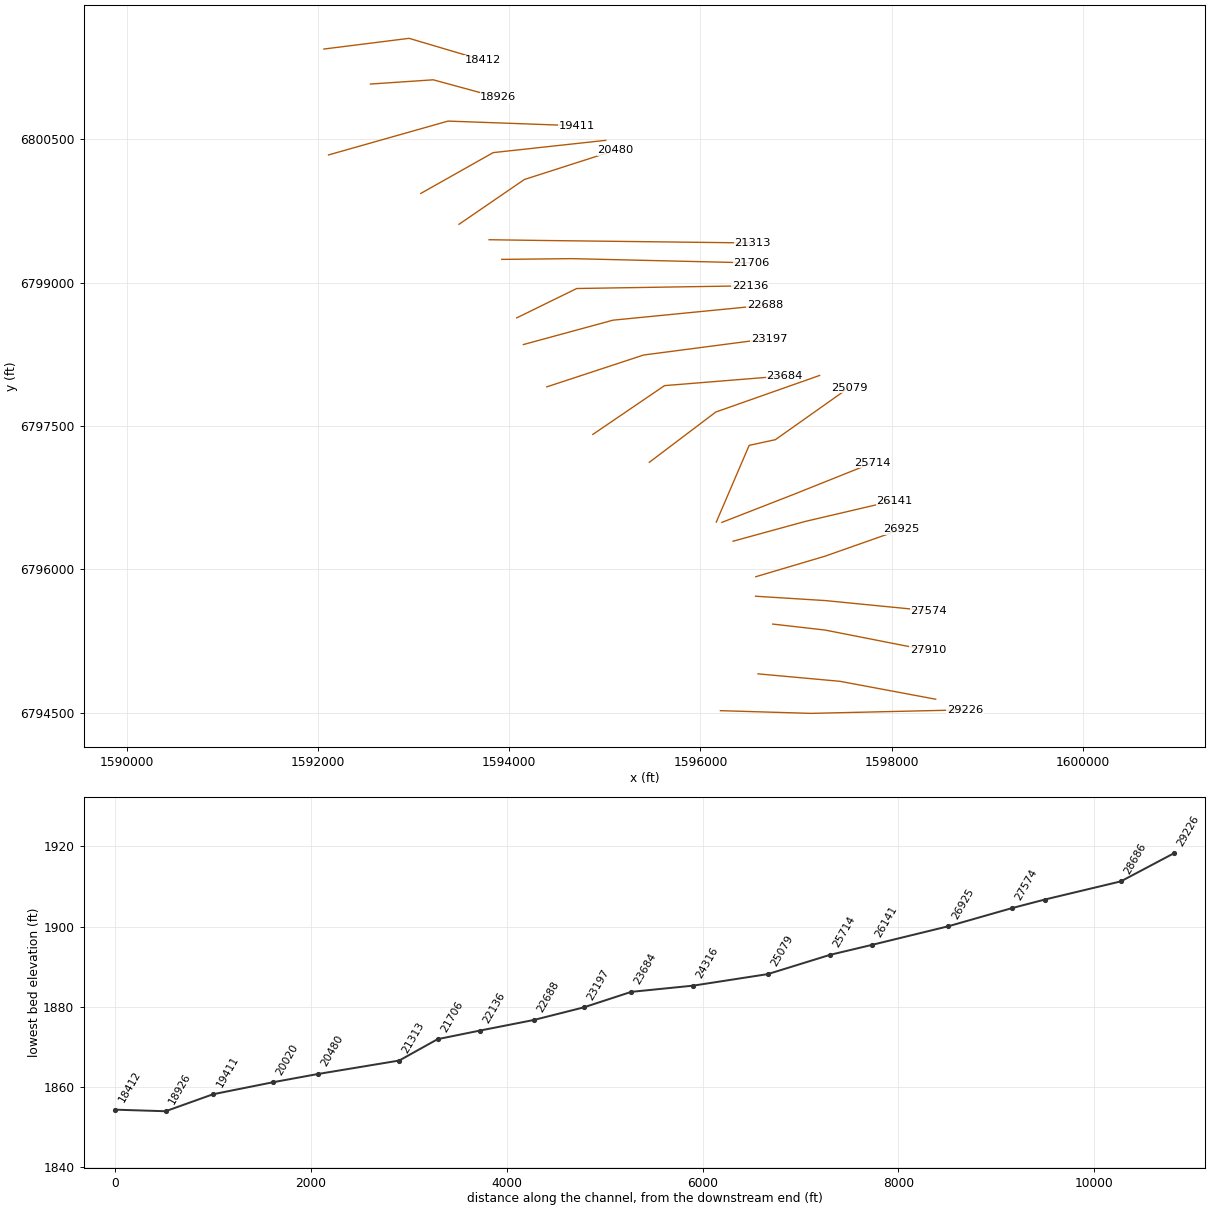
HEC-RAS study Elm 01 78.prj: Elm 01 78 Base Level Engineering

--- Elm 01 78.g01 (geometry) --- (continued)

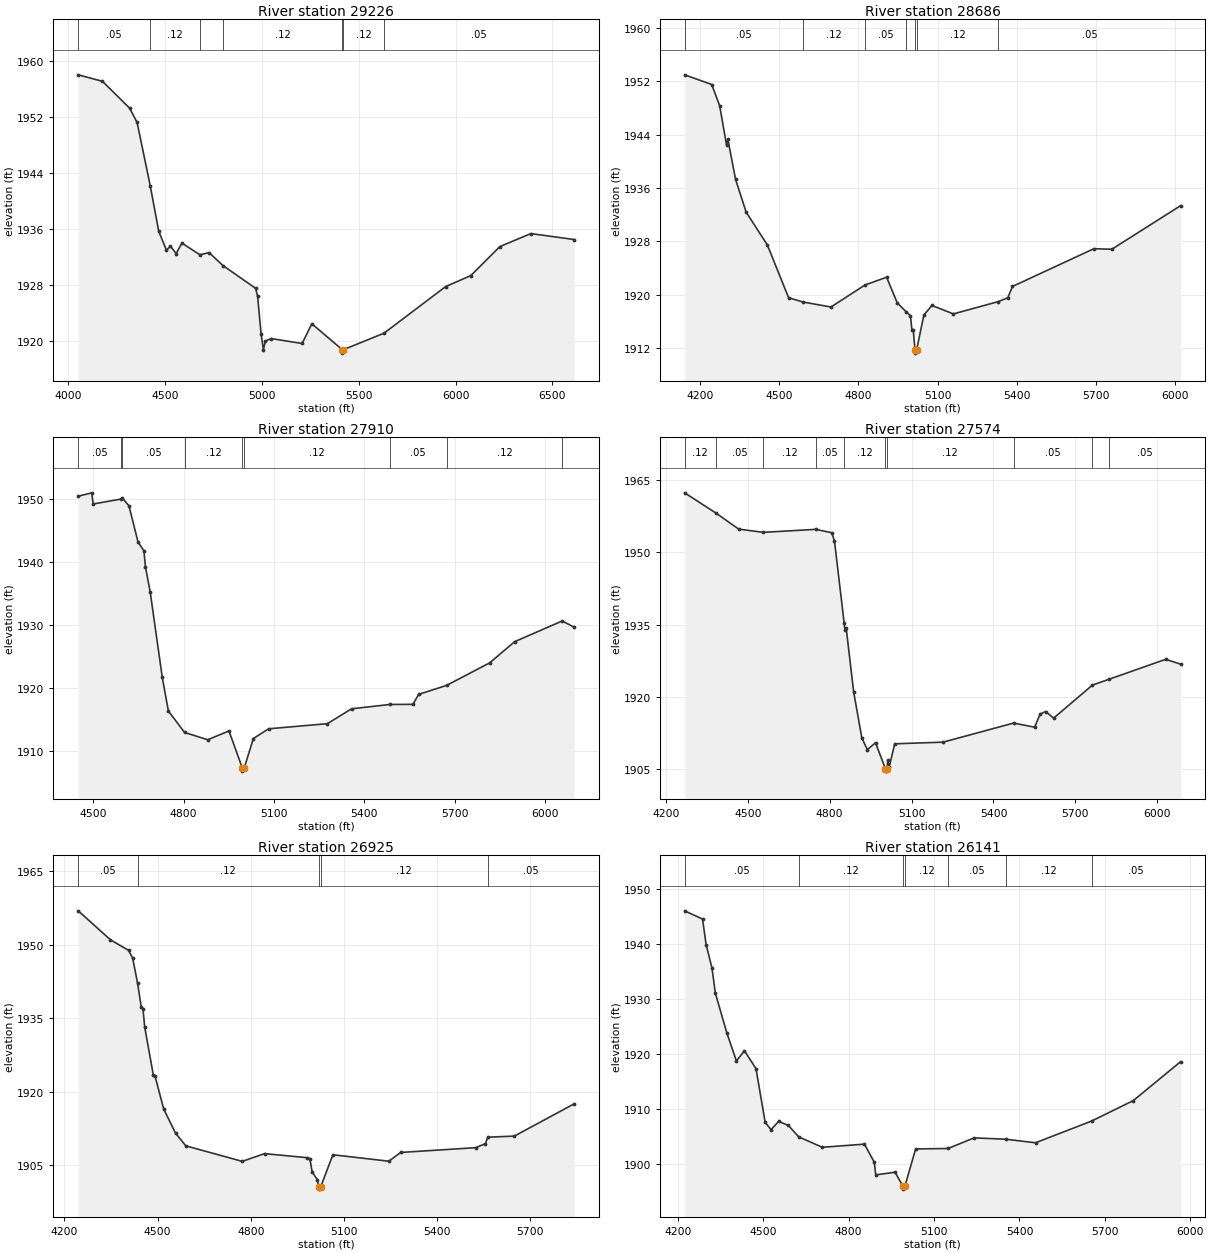
Type RM Length L Ch R = 1,29226,540,540,540
BEGIN DESCRIPTION:
Elm 01 78 29439.88
END DESCRIPTION:
XS GIS Cut Line= 3
      1596209.75      6794522.19      1597156.53      6794493.88
      1598768.40      6794530.87
#Sta/Elev= 30
  4052.8 1958.08  4178.1 1957.15  4318.2 1953.31  4356.7 1951.27  4424.8 1942.17
  4468.2 1935.72  4508.3 1932.98  4528.3 1933.58  4558.3 1932.52  4588.3 1934.01
  4680.8 1932.34  4728.4 1932.65  4799.7 1930.80  4968.5 1927.54  4978.5 1926.42
  4996.7 1920.99  5008.5 1918.78  5018.5 1919.98  5048.5 1920.35  5208.5 1919.65
  5258.5 1922.47  5415.4 1918.77  5415.9 1918.27  5421.7 1918.77  5630.8 1921.12
  5948.7 1927.78  6078.8 1929.36  6228.8 1933.51  6388.8 1935.37  6612.3 1934.52
#Mann=7,-1,0
  4052.8    0.05       0  4424.8    0.12       0  4680.8    0.05       0
  4799.7    0.12       0  5415.4    0.07       0  5421.7    0.12       0
  5630.8    0.05       0
Bank Sta=5415.4,5421.7
Exp/Cntr=0.3,0.1

Type RM Length L Ch R = 1,28686,776,776,776
BEGIN DESCRIPTION:
Elm 01 78 28686.25
END DESCRIPTION:
XS GIS Cut Line= 3
      1596602.97      6794907.46      1597460.65      6794829.33
      1598461.24      6794642.05
#Sta/Elev= 30
  4142.0 1952.94  4244.5 1951.49  4274.6 1948.31  4300.6 1942.44  4305.6 1943.31
  4334.8 1937.30  4375.0 1932.38  4455.3 1927.48  4535.7 1919.59  4589.4 1918.95
  4696.3 1918.19  4825.0 1921.48  4907.2 1922.65  4947.4 1918.81  4981.9 1917.45
  4997.6 1916.89  5002.9 1914.79  5008.0 1914.79  5014.7 1911.79  5015.2 1911.29
  5021.0 1911.79  5048.4 1917.00  5078.9 1918.42  5160.3 1917.16  5330.4 1919.00
  5366.3 1919.58  5384.1 1921.27  5692.1 1926.91  5760.5 1926.84  6021.2 1933.36
#Mann=7,-1,0
  4142.0    0.05       0  4589.4    0.12       0  4825.0    0.05       0
  4981.9    0.12       0  5014.7    0.07       0  5021.0    0.12       0
  5330.4    0.05       0
Bank Sta=5014.7,5021
Exp/Cntr=0.3,0.1

Type RM Length L Ch R = 1,27910,336,336,336
BEGIN DESCRIPTION:
Elm 01 78 27909.68
END DESCRIPTION:
XS GIS Cut Line= 3
      1596757.57      6795428.29      1597304.40      6795365.79
      1598380.37      6795154.07
#Sta/Elev= 30
  4449.8 1950.39  4494.4 1950.93  4499.5 1949.16  4593.2 1949.95  4596.2 1950.11
  4618.3 1948.87  4648.5 1943.11  4668.1 1941.72  4673.1 1939.17  4688.8 1935.22
  4729.0 1921.64  4749.2 1916.31  4802.9 1912.90  4880.0 1911.74  4950.5 1913.14
  4994.7 1907.26  4995.2 1906.76  5001.2 1907.26  5031.4 1911.93  5082.3 1913.48
  5277.3 1914.29  5357.5 1916.65  5484.8 1917.34  5561.4 1917.36  5580.5 1918.94
  5673.3 1920.37  5816.1 1923.94  5899.0 1927.30  6056.9 1930.59  6096.8 1929.61
#Mann=9,-1,0
  4449.8    0.05       0  4593.2    0.12       0  4596.2    0.05       0
  4802.9    0.12       0  4994.7    0.07       0  5001.2    0.12       0
  5484.8    0.05       0  5673.3    0.12       0  6056.9    0.05       0
Bank Sta=4994.7,5001.2
Exp/Cntr=0.3,0.1

Type RM Length L Ch R = 1,27574,649,649,649
BEGIN DESCRIPTION:
Elm 01 78 27574.26
END DESCRIPTION:
XS GIS Cut Line= 3
      1596577.38      6795719.78      1597306.54      6795674.21
      1598387.24      6795567.88
#Sta/Elev= 30
  4269.1 1962.37  4382.0 1958.23  4467.1 1954.84  4557.0 1954.17  4748.9 1954.79
  4807.8 1954.09  4817.8 1952.35  4853.4 1935.27  4855.8 1933.97  4860.8 1934.26
  4887.9 1921.10  4918.0 1911.52  4938.0 1909.08  4968.1 1910.50  5004.3 1905.12
  5004.8 1904.62  5010.9 1905.12  5012.6 1906.91  5018.2 1905.46  5038.3 1910.29
  5215.2 1910.63  5473.6 1914.59  5550.8 1913.74  5570.9 1916.44  5591.0 1916.99
  5620.5 1915.62  5762.7 1922.48  5821.7 1923.65  6030.7 1927.82  6085.6 1926.82
#Mann=10,-1,0
  4269.1    0.12       0  4382.0    0.05       0  4557.0    0.12       0
  4748.9    0.05       0  4853.4    0.12       0  5004.3    0.07       0
  5010.9    0.12       0  5473.6    0.05       0  5762.7    0.12       0
  5821.7    0.05       0
Bank Sta=5004.3,5010.9
Exp/Cntr=0.3,0.1

Type RM Length L Ch R = 1,26925,784,784,784
BEGIN DESCRIPTION:
Elm 01 78 27047.52
END DESCRIPTION:
XS GIS Cut Line= 3
      1596579.72      6795923.77      1597304.17      6796138.84
      1598097.88      6796418.39
#Sta/Elev= 30
  4244.3 1956.94  4348.0 1951.03  4406.3 1948.87  4419.6 1947.30  4435.5 1942.16
  4447.6 1937.20  4452.8 1936.96  4458.4 1933.21  4486.0 1923.48  4491.3 1923.29
  4519.3 1916.52  4557.7 1911.53  4590.9 1908.94  4772.6 1905.77  4844.4 1907.35
  4982.3 1906.52  4990.4 1906.32  4997.8 1903.60  5014.7 1902.02  5018.8 1900.60
  5019.3 1900.10  5025.4 1900.60  5064.5 1907.12  5244.7 1905.80  5282.6 1907.59
  5525.0 1908.57  5555.9 1909.40  5563.2 1910.71  5648.8 1910.93  5841.5 1917.52
#Mann=5,-1,0
  4244.3    0.05       0  4435.5    0.12       0  5018.8    0.07       0
  5025.4    0.12       0  5563.2    0.05       0
Bank Sta=5018.8,5025.4
Exp/Cntr=0.3,0.1

Type RM Length L Ch R = 1,26141,427,427,427
BEGIN DESCRIPTION:
Elm 01 78 26140.98
END DESCRIPTION:
XS GIS Cut Line= 3
      1596342.39      6796295.57      1597092.38      6796501.30
      1598031.21      6796721.05
#Sta/Elev= 30
  4224.1 1945.98  4286.9 1944.48  4299.4 1939.86  4320.1 1935.56  4331.7 1931.05
  4372.0 1923.83  4405.8 1918.71  4434.2 1920.57  4474.7 1917.29  4506.8 1907.55
  4527.5 1906.23  4554.0 1907.73  4588.5 1906.99  4624.5 1904.93  4707.4 1903.03
  4855.6 1903.60  4890.1 1900.30  4895.2 1898.02  4963.0 1898.50  4990.8 1895.93
  4991.3 1895.43  4997.4 1895.93  5035.3 1902.73  5149.0 1902.81  5240.7 1904.74
  5351.0 1904.50  5456.4 1903.85  5654.0 1907.81  5799.7 1911.51  5966.0 1918.58
#Mann=7,-1,0
  4224.1    0.05       0  4624.5    0.12       0  4990.8    0.07       0
  4997.4    0.12       0  5149.0    0.05       0  5351.0    0.12       0
  5654.0    0.05       0
Bank Sta=4990.8,4997.4
Exp/Cntr=0.3,0.1

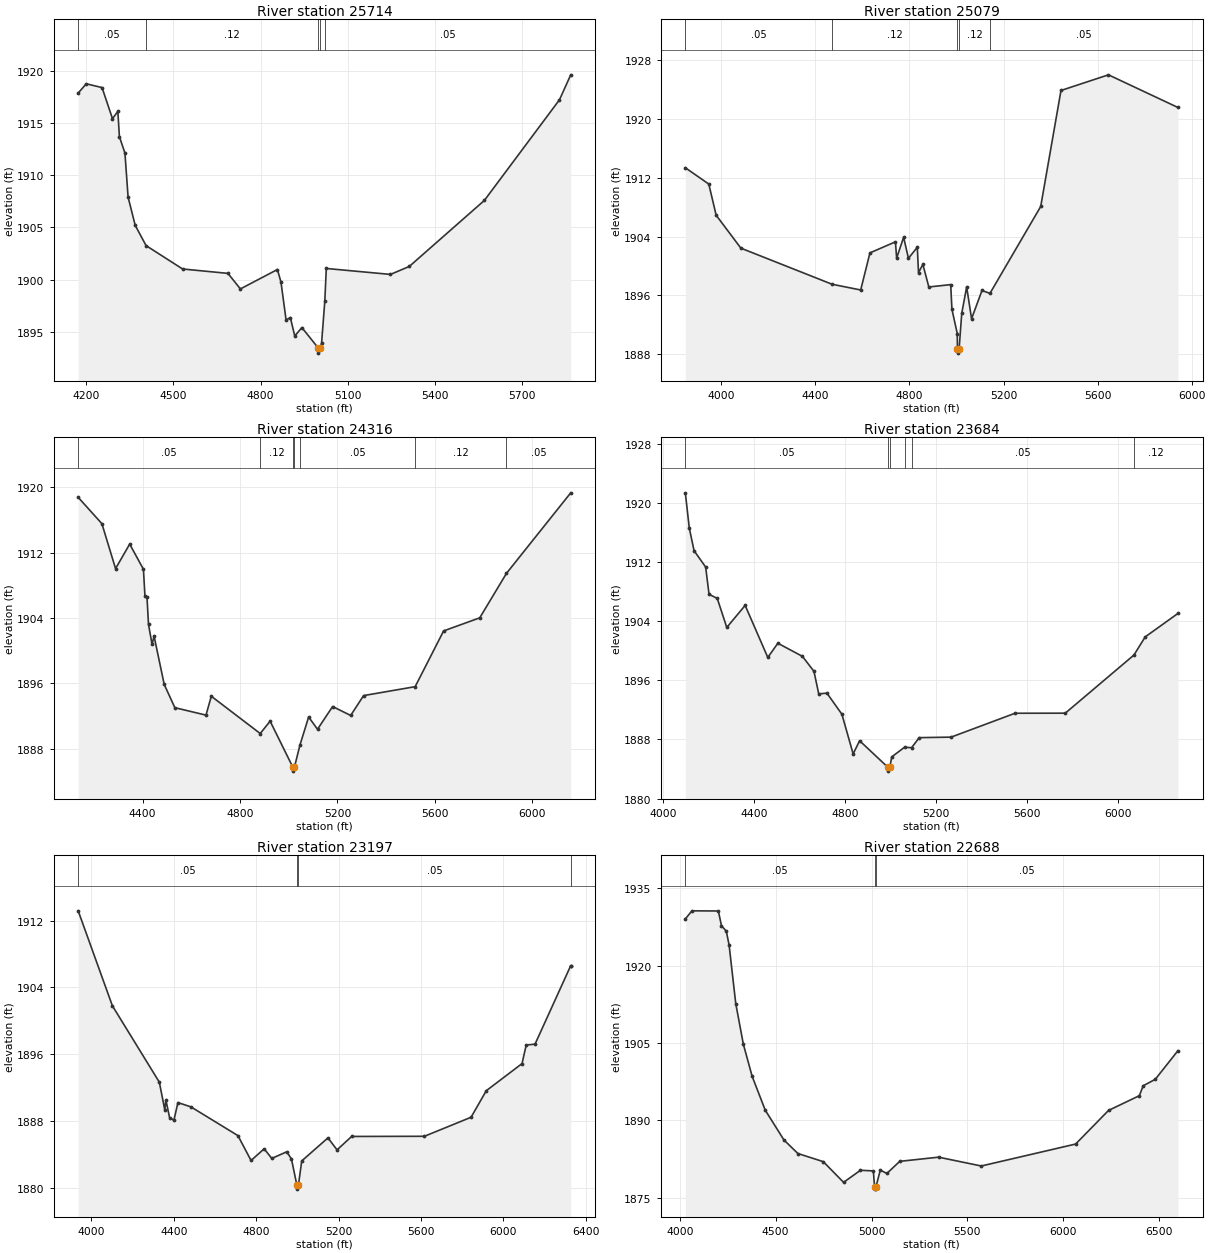
Type RM Length L Ch R = 1,25714,635,635,635
BEGIN DESCRIPTION:
Elm 01 78 25714.35
END DESCRIPTION:
XS GIS Cut Line= 3
      1596225.11      6796492.54      1596999.39      6796794.61
      1597800.71      6797115.49
#Sta/Elev= 30
  4172.5 1917.86  4200.3 1918.75  4254.6 1918.39  4290.5 1915.41  4309.0 1916.11
  4314.3 1913.69  4333.4 1912.11  4344.2 1907.90  4368.7 1905.19  4406.1 1903.25
  4531.7 1901.01  4687.6 1900.59  4730.6 1899.10  4857.8 1900.96  4870.1 1899.76
  4887.7 1896.12  4902.3 1896.36  4917.5 1894.59  4942.0 1895.40  4998.1 1893.45
  4998.6 1892.95  5004.8 1893.45  5009.7 1893.88  5020.9 1897.94  5026.0 1901.06
  5246.7 1900.49  5311.3 1901.25  5569.8 1907.58  5828.1 1917.22  5866.8 1919.61
#Mann=5,-1,0
  4172.5    0.05       0  4406.1    0.12       0  4998.1    0.07       0
  5004.8    0.12       0  5020.9    0.05       0
Bank Sta=4998.1,5004.8
Exp/Cntr=0.3,0.1

Type RM Length L Ch R = 1,25079,763,763,763
BEGIN DESCRIPTION:
Elm 01 78 25078.93
END DESCRIPTION:
XS GIS Cut Line= 4
      1596166.74      6796496.26      1596510.49      6797298.34
      1596784.72      6797358.11      1597553.45      6797901.85
#Sta/Elev= 30
  3846.7 1913.37  3946.5 1911.15  3977.8 1906.91  4083.0 1902.43  4470.8 1897.52
  4592.5 1896.74  4631.9 1901.79  4740.3 1903.29  4745.4 1901.07  4775.1 1903.91
  4795.6 1901.05  4833.3 1902.55  4838.4 1899.11  4857.0 1900.22  4882.3 1897.15
  4975.4 1897.47  4980.5 1894.13  5003.2 1890.82  5004.0 1888.65  5004.5 1888.15
  5010.9 1888.65  5022.3 1893.56  5043.2 1897.16  5064.1 1892.83  5108.4 1896.67
  5142.3 1896.28  5358.2 1908.10  5444.4 1923.88  5646.3 1926.01  5941.6 1921.57
#Mann=5,-1,0
  3846.7    0.05       0  4470.8    0.12       0  5004.0    0.07       0
  5010.9    0.12       0  5142.3    0.05       0
Bank Sta=5004,5010.9
Exp/Cntr=0.3,0.1

Type RM Length L Ch R = 1,24316,632,632,632
BEGIN DESCRIPTION:
Elm 01 78 24316.45
END DESCRIPTION:
XS GIS Cut Line= 3
      1595466.21      6797121.25      1596161.54      6797647.30
      1597247.44      6798030.10
#Sta/Elev= 30
  4135.2 1918.76  4232.6 1915.54  4288.8 1910.04  4346.8 1913.04  4403.3 1909.96
  4409.6 1906.63  4417.8 1906.61  4424.1 1903.21  4438.7 1900.78  4447.0 1901.78
  4488.6 1895.88  4532.3 1893.03  4660.3 1892.12  4682.1 1894.43  4883.0 1889.87
  4923.7 1891.38  5016.7 1885.77  5017.2 1885.27  5023.7 1885.77  5046.4 1888.48
  5082.0 1891.89  5118.3 1890.39  5180.4 1893.17  5254.6 1892.08  5307.7 1894.51
  5519.4 1895.60  5636.4 1902.42  5784.8 1904.02  5894.5 1909.46  6158.5 1919.31
#Mann=7,-1,0
  4135.2    0.05       0  4883.0    0.12       0  5016.7    0.07       0
  5023.7    0.12       0  5046.4    0.05       0  5519.4    0.12       0
  5894.5    0.05       0
Bank Sta=5016.7,5023.7
Exp/Cntr=0.3,0.1

Type RM Length L Ch R = 1,23684,487,487,487
BEGIN DESCRIPTION:
Elm 01 78 23684.18
END DESCRIPTION:
XS GIS Cut Line= 3
      1594875.51      6797413.21      1595625.51      6797923.63
      1596878.09      6798025.19
#Sta/Elev= 30
  4097.3 1921.37  4114.8 1916.58  4135.7 1913.54  4186.6 1911.33  4201.5 1907.64
  4237.5 1907.09  4279.4 1903.16  4360.1 1906.14  4459.6 1899.10  4503.8 1901.02
  4611.6 1899.25  4662.4 1897.22  4683.4 1894.17  4719.3 1894.27  4785.1 1891.42
  4834.5 1886.05  4863.0 1887.83  4987.9 1884.22  4988.4 1883.72  4995.7 1884.22
  5004.0 1885.64  5060.2 1886.95  5091.3 1886.89  5124.9 1888.25  5264.9 1888.32
  5545.8 1891.55  5766.5 1891.56  6068.3 1899.43  6117.6 1901.88  6261.2 1905.05
#Mann=6,-1,0
  4097.3    0.05       0  4987.9    0.05       0  4995.7    0.05       0
  5060.2    0.12       0  5091.3    0.05       0  6068.3    0.12       0
Bank Sta=4987.9,4995.7
Exp/Cntr=0.3,0.1

Type RM Length L Ch R = 1,23197,509,509,509
BEGIN DESCRIPTION:
Elm 01 78 23196.99
END DESCRIPTION:
XS GIS Cut Line= 3
      1594393.72      6797910.60      1595406.76      6798243.94
      1596719.28      6798415.82
#Sta/Elev= 30
  3936.4 1913.18  4102.5 1901.80  4330.3 1892.65  4356.8 1889.32  4362.0 1890.53
  4379.9 1888.42  4401.0 1888.09  4420.4 1890.21  4483.9 1889.69  4711.7 1886.25
  4775.3 1883.27  4838.9 1884.67  4875.9 1883.52  4948.4 1884.31  4971.3 1883.46
  4997.5 1880.34  4998.0 1879.84  5005.3 1880.34  5021.3 1883.22  5148.5 1885.98
  5192.7 1884.54  5263.3 1886.15  5616.5 1886.17  5843.0 1888.45  5916.8 1891.63
  6090.3 1894.88  6110.5 1897.10  6153.4 1897.21  6326.2 1906.59  6326.6 1906.59
#Mann=4,-1,0
  3936.4    0.05       0  4997.5    0.05       0  5005.3    0.05       0
  6326.2    0.12       0
Bank Sta=4997.5,5005.3
Exp/Cntr=0.3,0.1

Type RM Length L Ch R = 1,22688,552,552,552
BEGIN DESCRIPTION:
Elm 01 78 22687.68
END DESCRIPTION:
XS GIS Cut Line= 3
      1594148.93      6798353.31      1595086.45      6798608.53
      1596674.95      6798764.77
#Sta/Elev= 30
  4029.4 1929.03  4063.9 1930.60  4201.5 1930.57  4217.8 1927.73  4243.0 1926.65
  4257.6 1923.98  4292.2 1912.65  4331.9 1904.76  4377.7 1898.55  4446.0 1891.99
  4543.5 1886.22  4616.1 1883.60  4748.6 1882.02  4854.4 1878.01  4942.2 1880.35
  5009.6 1880.23  5015.7 1877.20  5016.2 1876.70  5023.6 1877.20  5045.8 1880.39
  5080.0 1879.73  5147.1 1882.08  5349.7 1882.89  5572.3 1881.18  6064.0 1885.43
  6235.5 1891.94  6396.3 1894.80  6416.4 1896.72  6479.3 1897.97  6597.2 1903.50
#Mann=3,-1,0
  4029.4    0.05       0  5015.7    0.03       0  5023.6    0.05       0
Bank Sta=5015.7,5023.6
Exp/Cntr=0.3,0.1

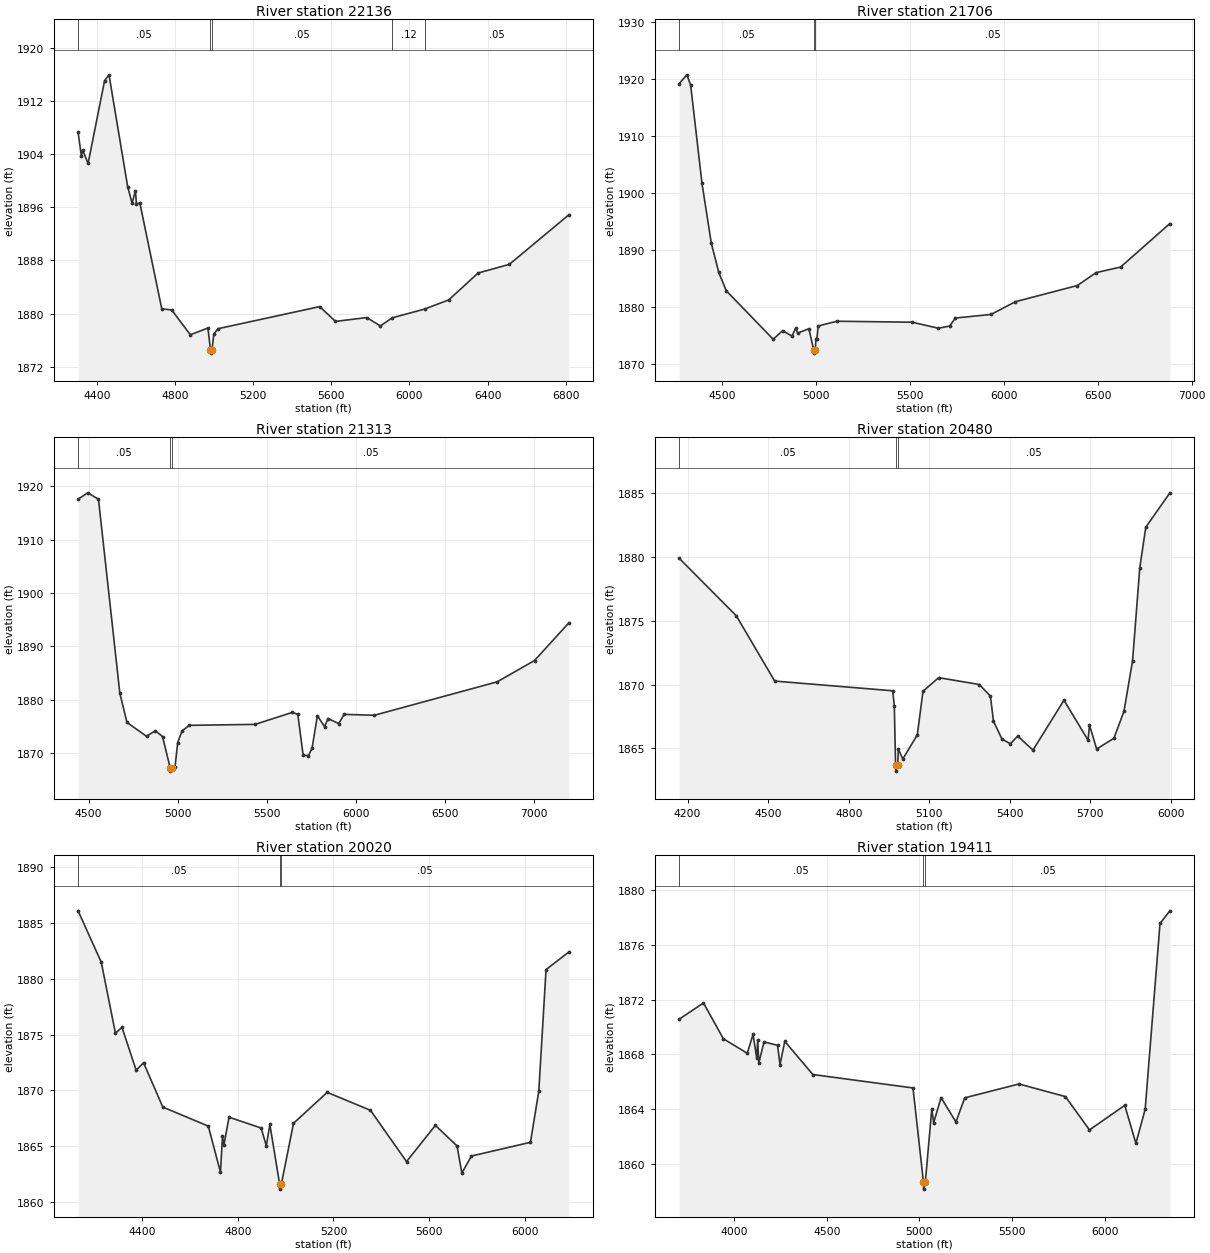
Type RM Length L Ch R = 1,22136,430,430,430
BEGIN DESCRIPTION:
Elm 01 78 22136.08
END DESCRIPTION:
XS GIS Cut Line= 3
      1594079.51      6798632.62      1594707.11      6798939.91
      1596519.60      6798968.55
#Sta/Elev= 30
  4304.3 1907.27  4321.5 1903.67  4327.5 1904.62  4355.6 1902.59  4440.0 1915.05
  4462.5 1915.92  4558.1 1899.09  4580.6 1896.60  4597.6 1898.49  4603.1 1896.43
  4620.1 1896.67  4732.6 1880.71  4783.2 1880.55  4878.8 1876.81  4968.8 1877.83
  4981.7 1874.55  4982.2 1874.05  4989.7 1874.55  4999.1 1876.94  5021.0 1877.73
  5541.0 1881.05  5621.1 1878.82  5781.1 1879.40  5851.1 1878.14  5911.6 1879.36
  6078.5 1880.69  6201.1 1882.06  6351.1 1886.10  6511.2 1887.41  6815.8 1894.87
#Mann=5,-1,0
  4304.3    0.05       0  4981.7    0.05       0  4989.7    0.05       0
  5911.6    0.12       0  6078.5    0.05       0
Bank Sta=4981.7,4989.7
Exp/Cntr=0.3,0.1

Type RM Length L Ch R = 1,21706,393,393,393
BEGIN DESCRIPTION:
Elm 01 78 21705.73
END DESCRIPTION:
XS GIS Cut Line= 3
      1593923.23      6799244.59      1594655.03      6799252.41
      1596537.87      6799208.13
#Sta/Elev= 30
  4268.8 1919.13  4310.6 1920.69  4330.6 1918.89  4390.6 1901.76  4440.6 1891.18
  4480.6 1886.05  4520.6 1882.84  4770.6 1874.35  4820.6 1875.85  4870.6 1874.91
  4890.6 1876.33  4900.6 1875.42  4960.6 1876.20  4986.6 1872.42  4987.1 1871.92
  4994.6 1872.42  4998.1 1874.46  5003.1 1874.46  5010.6 1876.68  5110.6 1877.51
  5510.8 1877.34  5650.8 1876.28  5710.8 1876.67  5740.8 1878.07  5930.9 1878.70
  6060.9 1880.93  6391.0 1883.77  6491.0 1886.03  6621.1 1887.00  6884.0 1894.63
#Mann=3,-1,0
  4268.8    0.05       0  4986.6    0.05       0  4994.6    0.05       0
Bank Sta=4986.6,4994.6
Exp/Cntr=0.3,0.1

Type RM Length L Ch R = 1,21313,833,833,833
BEGIN DESCRIPTION:
Elm 01 78 21313.38
END DESCRIPTION:
XS GIS Cut Line= 3
      1593790.44      6799450.32      1594350.34      6799442.51
      1596548.23      6799416.47
#Sta/Elev= 30
  4440.6 1917.60  4495.2 1918.79  4555.2 1917.59  4675.2 1881.21  4715.2 1875.72
  4825.2 1873.11  4875.2 1874.17  4915.2 1873.05  4958.8 1867.08  4959.3 1866.58
  4966.8 1867.08  4985.2 1867.33  5000.4 1871.94  5025.2 1874.14  5065.2 1875.17
  5435.2 1875.35  5645.3 1877.61  5675.3 1877.22  5705.3 1869.57  5735.3 1869.50
  5755.3 1870.86  5785.3 1876.98  5825.3 1874.93  5845.3 1876.44  5905.3 1875.50
  5935.3 1877.23  6105.3 1877.06  6795.3 1883.33  7005.4 1887.33  7198.6 1894.41
#Mann=3,-1,0
  4440.6    0.05       0  4958.8    0.03       0  4966.8    0.05       0
Bank Sta=4958.8,4966.8
Exp/Cntr=0.3,0.1

Type RM Length L Ch R = 1,20480,460,460,460
BEGIN DESCRIPTION:
Elm 01 78 20480.48
END DESCRIPTION:
XS GIS Cut Line= 3
      1593475.62      6799611.97      1594159.63      6800080.70
      1595110.49      6800386.09
#Sta/Elev= 30
  4168.2 1879.91  4381.0 1875.40  4524.4 1870.27  4963.8 1869.51  4969.8 1868.34
  4974.6 1863.71  4975.1 1863.21  4982.7 1863.71  4984.8 1864.94  5001.4 1864.16
  5055.6 1866.06  5076.6 1869.47  5135.0 1870.54  5286.6 1870.00  5327.7 1869.09
  5339.1 1867.13  5370.7 1865.73  5402.4 1865.35  5429.2 1865.96  5486.2 1864.86
  5601.7 1868.77  5691.3 1865.64  5696.6 1866.83  5723.4 1864.94  5787.7 1865.79
  5825.0 1867.89  5857.1 1871.87  5884.0 1879.16  5906.3 1882.33  5996.1 1885.03
#Mann=3,-1,0
  4168.2    0.05       0  4974.6    0.05       0  4982.7    0.05       0
Bank Sta=4974.6,4982.7
Exp/Cntr=0.3,0.1

Type RM Length L Ch R = 1,20020,609,609,609
BEGIN DESCRIPTION:
Elm 01 78 20019.89
END DESCRIPTION:
XS GIS Cut Line= 3
      1593076.33      6799934.89      1593833.24      6800361.95
      1595010.17      6800490.41
#Sta/Elev= 30
  4131.9 1886.11  4228.9 1881.50  4288.1 1875.13  4315.5 1875.66  4374.7 1871.82
  4405.9 1872.48  4486.3 1868.51  4676.6 1866.80  4727.4 1862.67  4735.9 1865.89
  4741.6 1865.08  4763.3 1867.60  4897.6 1866.63  4919.3 1865.03  4934.1 1866.95
  4974.5 1861.65  4975.0 1861.15  4982.6 1861.65  5032.9 1867.05  5173.8 1869.83
  5354.8 1868.22  5505.7 1863.62  5626.4 1866.87  5717.0 1865.02  5737.1 1862.59
  5777.3 1864.12  6024.1 1865.35  6059.0 1869.95  6089.2 1880.84  6184.9 1882.42
#Mann=3,-1,0
  4131.9    0.05       0  4974.5    0.05       0  4982.6    0.05       0
Bank Sta=4974.5,4982.6
Exp/Cntr=0.3,0.1

Type RM Length L Ch R = 1,19411,485,485,485
BEGIN DESCRIPTION:
Elm 01 78 19411.37
END DESCRIPTION:
XS GIS Cut Line= 3
      1592111.06      6800337.66      1593361.02      6800691.82
      1594708.28      6800643.20
#Sta/Elev= 30
  3703.7 1870.56  3835.5 1871.75  3942.5 1869.14  4071.6 1868.08  4102.8 1869.46
  4122.6 1867.72  4127.8 1869.07  4133.9 1867.36  4161.7 1868.91  4234.8 1868.66
  4248.3 1867.26  4273.9 1868.95  4425.2 1866.53  4965.4 1865.55  5021.9 1858.67
  5022.4 1858.17  5031.9 1858.67  5066.9 1864.04  5076.9 1863.02  5116.9 1864.84
  5197.0 1863.07  5244.7 1864.83  5537.2 1865.84  5787.4 1864.92  5917.4 1862.49
  6107.6 1864.28  6167.6 1861.51  6217.6 1863.99  6297.7 1877.55  6351.0 1878.47
#Mann=3,-1,0
  3703.7    0.05       0  5021.9    0.03       0  5031.9    0.05       0
Bank Sta=5021.9,5031.9
Exp/Cntr=0.3,0.1

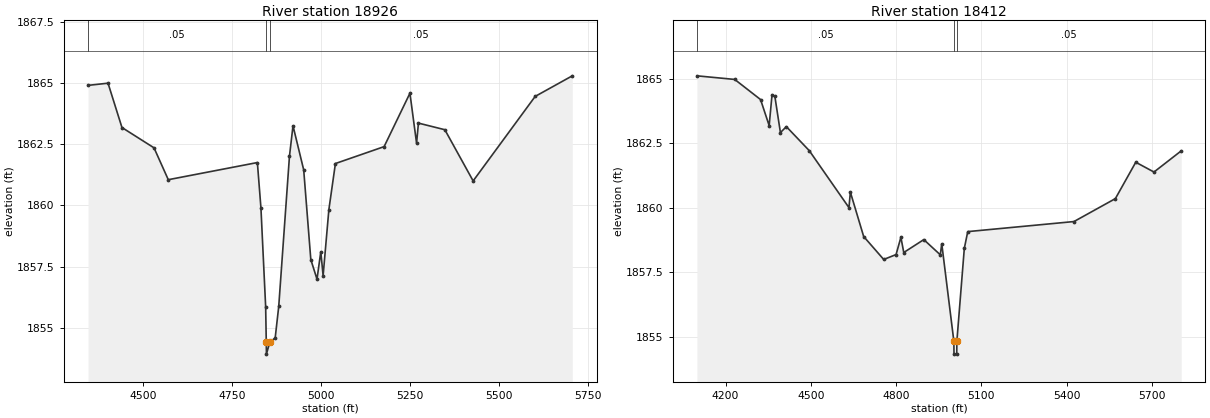
Type RM Length L Ch R = 1,18926,514,514,514
BEGIN DESCRIPTION:
Elm 01 78 18926.23
END DESCRIPTION:
XS GIS Cut Line= 3
      1592549.69      6801079.49      1593205.98      6801123.76
      1593885.70      6800938.86
#Sta/Elev= 30
  4344.7 1864.90  4401.0 1864.99  4440.2 1863.18  4530.4 1862.35  4570.5 1861.05
  4821.1 1861.75  4831.1 1859.90  4844.4 1855.86  4846.1 1854.43  4846.6 1853.93
  4856.2 1854.43  4871.2 1854.59  4881.2 1855.88  4911.3 1862.00  4921.3 1863.25
  4951.4 1861.45  4971.4 1857.79  4988.8 1856.99  4999.5 1858.11  5006.0 1857.13
  5022.2 1859.83  5040.6 1861.71  5177.6 1862.40  5250.2 1864.58  5268.9 1862.54
  5274.1 1863.36  5348.4 1863.09  5428.0 1861.00  5602.5 1864.45  5706.9 1865.29
#Mann=3,-1,0
  4344.7    0.05       0  4846.1    0.03       0  4856.2    0.05       0
Bank Sta=4846.1,4856.2
Exp/Cntr=0.3,0.1

Type RM Length L Ch R = 1,18412,341,341,341
BEGIN DESCRIPTION:
Elm 01 78 18412.14
END DESCRIPTION:
XS GIS Cut Line= 3
      1592062.70      6801445.80      1592953.38      6801557.79
      1593726.85      6801328.61
#Sta/Elev= 30
  4099.2 1865.11  4232.3 1864.97  4323.2 1864.19  4353.5 1863.18  4363.6 1864.38
  4373.6 1864.31  4393.1 1862.91  4414.0 1863.14  4494.6 1862.21  4634.3 1860.00
  4639.3 1860.60  4686.1 1858.88  4756.6 1857.99  4800.1 1858.18  4817.1 1858.85
  4827.2 1858.26  4897.7 1858.76  4955.8 1858.17  4960.9 1858.60  5003.5 1854.82
  5004.0 1854.32  5013.6 1854.32  5014.1 1854.82  5040.3 1858.42  5052.4 1859.07
  5426.2 1859.46  5572.0 1860.35  5643.7 1861.76  5707.8 1861.38  5803.6 1862.20
#Mann=3,-1,0
  4099.2    0.05       0  5003.5    0.03       0  5014.1    0.05       0
Bank Sta=5003.5,5014.1
Exp/Cntr=0.3,0.1