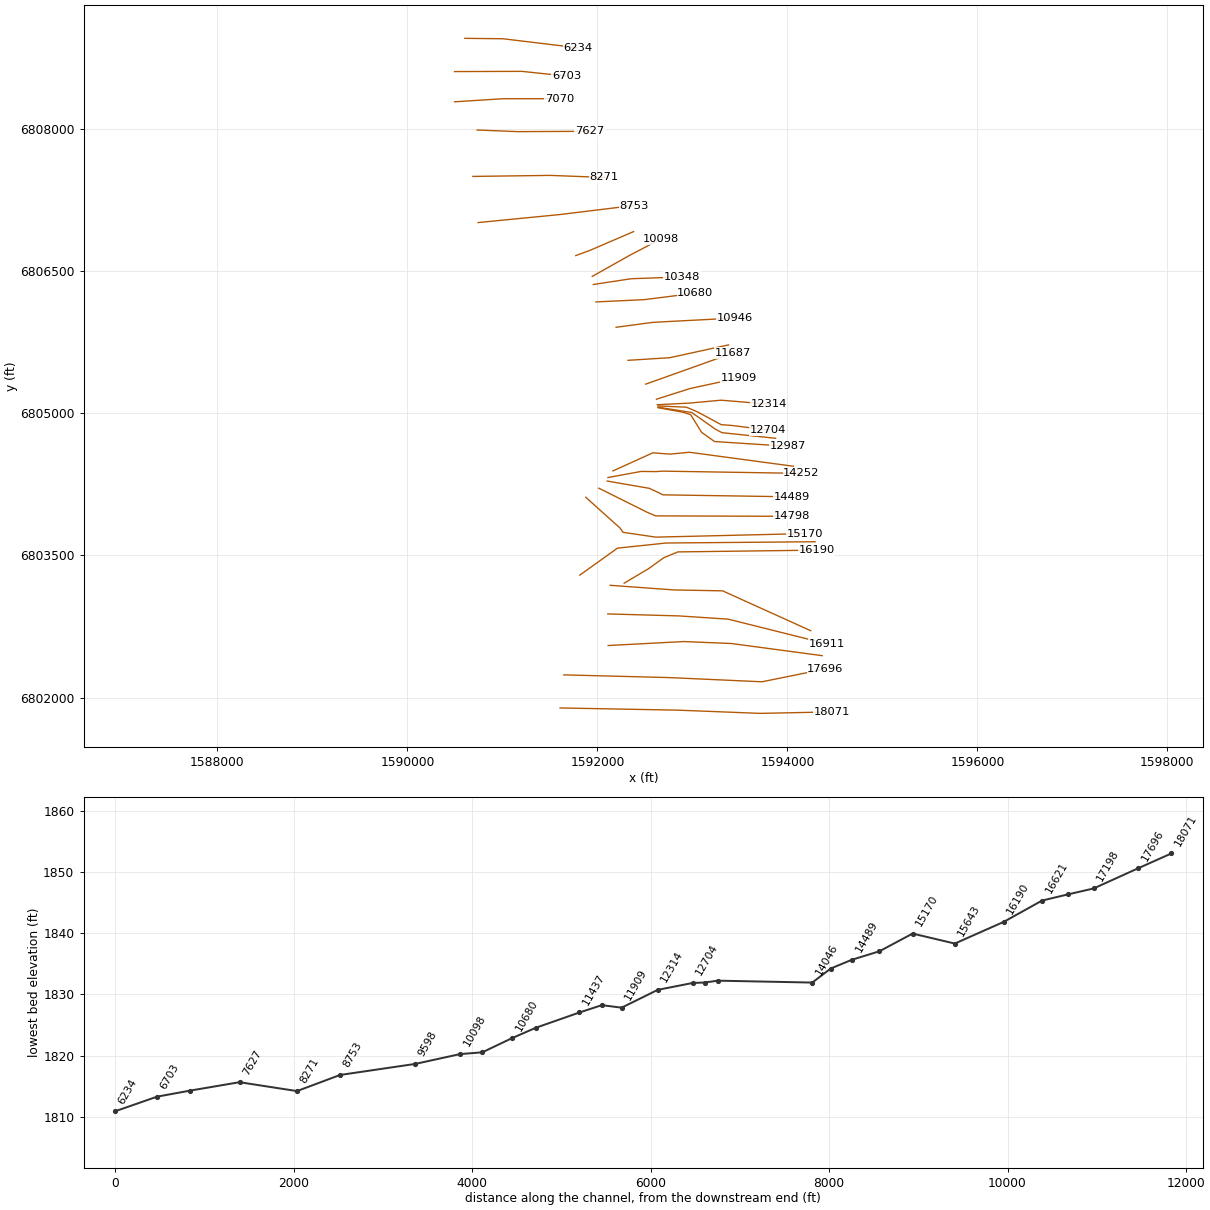
HEC-RAS study Elm 01 78.prj: Elm 01 78 Base Level Engineering

--- Elm 01 78.g01 (geometry) --- (continued)

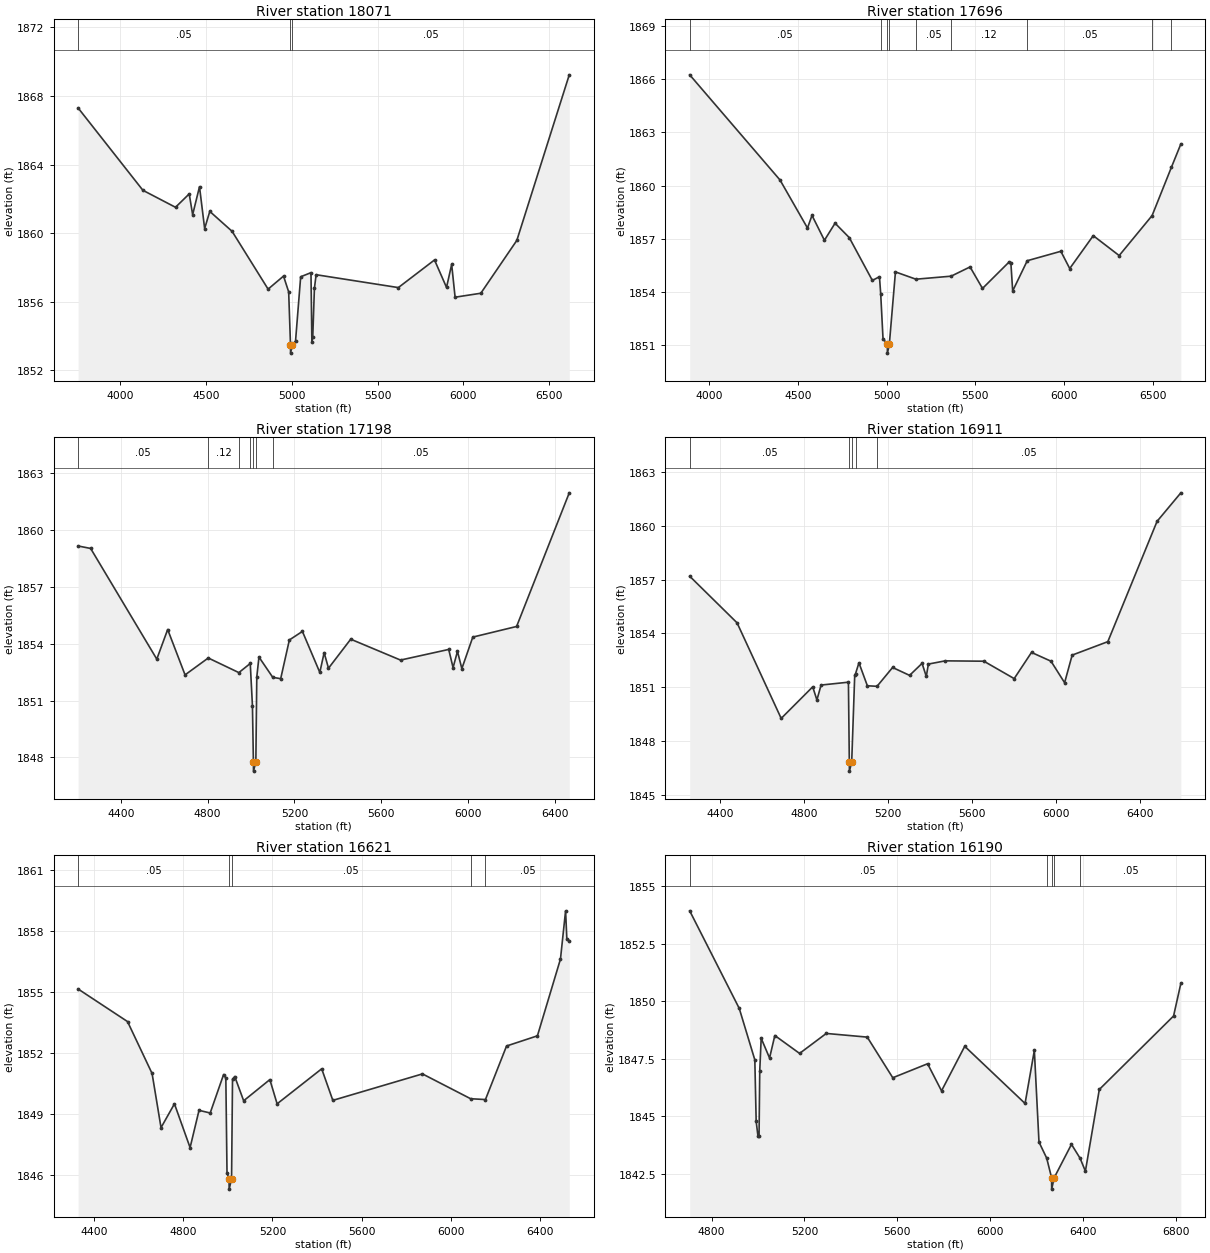
Type RM Length L Ch R = 1,18071,375,375,375
BEGIN DESCRIPTION:
Elm 01 78 18071.07
END DESCRIPTION:
XS GIS Cut Line= 4
      1591607.02      6801891.12      1592851.81      6801867.68
      1593711.19      6801833.83      1594470.78      6801849.44
#Sta/Elev= 30
  3752.7 1867.30  4130.7 1862.50  4320.8 1861.51  4400.8 1862.29  4420.8 1861.08
  4460.8 1862.71  4490.8 1860.27  4520.8 1861.27  4650.8 1860.11  4860.9 1856.74
  4950.9 1857.50  4980.9 1856.58  4991.5 1853.51  4992.0 1853.01  5002.1 1853.51
  5020.9 1853.71  5050.9 1857.46  5111.0 1857.70  5116.3 1853.66  5121.3 1853.93
  5131.0 1856.78  5141.0 1857.58  5620.6 1856.83  5831.5 1858.44  5901.6 1856.84
  5931.6 1858.18  5951.6 1856.27  6101.6 1856.50  6311.7 1859.58  6617.5 1869.23
#Mann=3,-1,0
  3752.7    0.05       0  4991.5    0.05       0  5002.1    0.05       0
Bank Sta=4991.5,5002.1
Exp/Cntr=0.3,0.1

Type RM Length L Ch R = 1,17696,498,498,498
BEGIN DESCRIPTION:
Elm 01 78 17695.95
END DESCRIPTION:
XS GIS Cut Line= 4
      1591646.07      6802240.08      1592758.06      6802211.43
      1593732.02      6802167.16      1594398.68      6802302.58
#Sta/Elev= 30
  3890.1 1866.23  4399.2 1860.31  4553.8 1857.61  4579.3 1858.32  4649.3 1856.92
  4709.3 1857.88  4789.3 1857.07  4919.4 1854.66  4959.4 1854.87  4966.4 1853.91
  4979.4 1851.39  5003.8 1851.07  5004.3 1850.57  5015.0 1851.07  5049.5 1855.14
  5164.8 1854.73  5363.2 1854.90  5469.9 1855.42  5540.0 1854.21  5690.1 1855.70
  5700.1 1855.62  5710.1 1854.07  5792.2 1855.77  5981.5 1856.30  6031.5 1855.33
  6164.1 1857.18  6310.1 1856.06  6495.7 1858.31  6604.2 1861.02  6657.7 1862.34
#Mann=9,-1,0
  3890.1    0.05       0  4966.4    0.12       0  5003.8    0.07       0
  5015.0    0.12       0  5164.8    0.05       0  5363.2    0.12       0
  5792.2    0.05       0  6495.7    0.12       0  6604.2    0.05       0
Bank Sta=5003.8,5015
Exp/Cntr=0.3,0.1

Type RM Length L Ch R = 1,17198,287,287,287
BEGIN DESCRIPTION:
Elm 01 78 17197.94
END DESCRIPTION:
XS GIS Cut Line= 4
      1592112.99      6802549.93      1592908.10      6802591.60
      1593407.94      6802571.24      1594365.42      6802442.88
#Sta/Elev= 30
  4203.3 1859.14  4261.1 1859.01  4565.8 1853.18  4615.9 1854.74  4696.0 1852.35
  4802.9 1853.24  4943.8 1852.47  4996.3 1852.95  5006.4 1850.72  5010.8 1847.78
  5011.3 1847.28  5022.1 1847.78  5026.4 1852.24  5036.4 1853.29  5100.0 1852.22
  5136.5 1852.15  5176.5 1854.19  5236.6 1854.64  5316.7 1852.48  5336.7 1853.52
  5356.7 1852.70  5459.1 1854.23  5688.5 1853.13  5910.5 1853.69  5930.6 1852.73
  5950.8 1853.59  5971.0 1852.68  6021.4 1854.34  6223.2 1854.90  6465.8 1861.94
#Mann=7,-1,0
  4203.3    0.05       0  4802.9    0.12       0  4943.8    0.05       0
  4996.3    0.12       0  5010.8    0.07       0  5022.1    0.12       0
  5100.0    0.05       0
Bank Sta=5010.8,5022.1
Exp/Cntr=0.3,0.1

Type RM Length L Ch R = 1,16911,290,290,290
BEGIN DESCRIPTION:
Elm 01 78 16910.96
END DESCRIPTION:
XS GIS Cut Line= 4
      1592109.44      6802883.27      1592856.02      6802862.43
      1593376.69      6802828.18      1594414.86      6802567.77
#Sta/Elev= 30
  4254.2 1857.19  4479.8 1854.59  4689.9 1849.26  4840.0 1851.02  4860.0 1850.29
  4880.0 1851.12  5010.1 1851.28  5014.4 1846.82  5014.9 1846.32  5025.7 1846.82
  5040.1 1851.66  5043.9 1851.75  5060.2 1852.36  5100.3 1851.08  5146.4 1851.05
  5220.5 1852.10  5301.4 1851.66  5360.8 1852.33  5380.9 1851.60  5390.9 1852.29
  5471.1 1852.47  5655.2 1852.45  5799.5 1851.48  5882.0 1852.94  5974.8 1852.45
  6039.6 1851.25  6075.6 1852.79  6245.4 1853.54  6479.9 1860.25  6593.2 1861.84
#Mann=5,-1,0
  4254.2    0.05       0  5014.4    0.05       0  5025.7    0.05       0
  5043.9    0.12       0  5146.4    0.05       0
Bank Sta=5014.4,5025.7
Exp/Cntr=0.3,0.1

Type RM Length L Ch R = 1,16621,431,431,431
BEGIN DESCRIPTION:
Elm 01 78 16622.15
END DESCRIPTION:
XS GIS Cut Line= 4
      1592133.84      6803185.35      1592800.46      6803136.74
      1593317.67      6803126.79      1594244.93      6802706.17
#Sta/Elev= 30
  4328.1 1855.14  4549.9 1853.54  4660.1 1850.99  4700.2 1848.33  4760.4 1849.50
  4830.6 1847.35  4870.7 1849.18  4920.8 1849.05  4981.0 1850.94  4991.0 1850.77
  4996.3 1846.10  5005.4 1845.81  5005.9 1845.31  5016.7 1845.81  5021.0 1850.71
  5031.0 1850.84  5071.0 1849.65  5188.5 1850.69  5221.1 1849.50  5421.1 1851.22
  5471.1 1849.67  5873.2 1850.97  6089.5 1849.75  6155.9 1849.71  6250.6 1852.34
  6389.1 1852.84  6492.5 1856.61  6515.5 1858.98  6521.1 1857.60  6532.0 1857.51
#Mann=5,-1,0
  4328.1    0.05       0  5005.4    0.05       0  5016.7    0.05       0
  6089.5    0.12       0  6155.9    0.05       0
Bank Sta=5005.4,5016.7
Exp/Cntr=0.3,0.1

Type RM Length L Ch R = 1,16190,547,547,547
BEGIN DESCRIPTION:
Elm 01 78 16189.65
END DESCRIPTION:
XS GIS Cut Line= 5
      1592281.38      6803207.93      1592538.31      6803360.70
      1592697.01      6803475.75      1592847.18      6803537.76
      1594306.36      6803556.48
#Sta/Elev= 30
  4705.5 1853.94  4919.1 1849.69  4986.2 1847.45  4992.0 1844.77  4999.6 1844.14
  5004.4 1844.14  5007.4 1846.96  5013.6 1848.39  5049.7 1847.53  5072.4 1848.51
  5179.1 1847.73  5294.1 1848.60  5470.7 1848.44  5580.7 1846.67  5730.7 1847.28
  5790.8 1846.10  5890.8 1848.04  6150.8 1845.55  6190.8 1847.86  6210.8 1843.87
  6244.0 1843.17  6265.0 1842.32  6265.5 1841.82  6276.5 1842.32  6350.8 1843.77
  6388.2 1843.16  6410.8 1842.60  6470.8 1846.16  6790.8 1849.36  6822.2 1850.78
#Mann=5,-1,0
  4705.5    0.05       0  6244.0    0.12       0  6265.0    0.05       0
  6276.5    0.12       0  6388.2    0.05       0
Bank Sta=6265,6276.5
Exp/Cntr=0.3,0.1

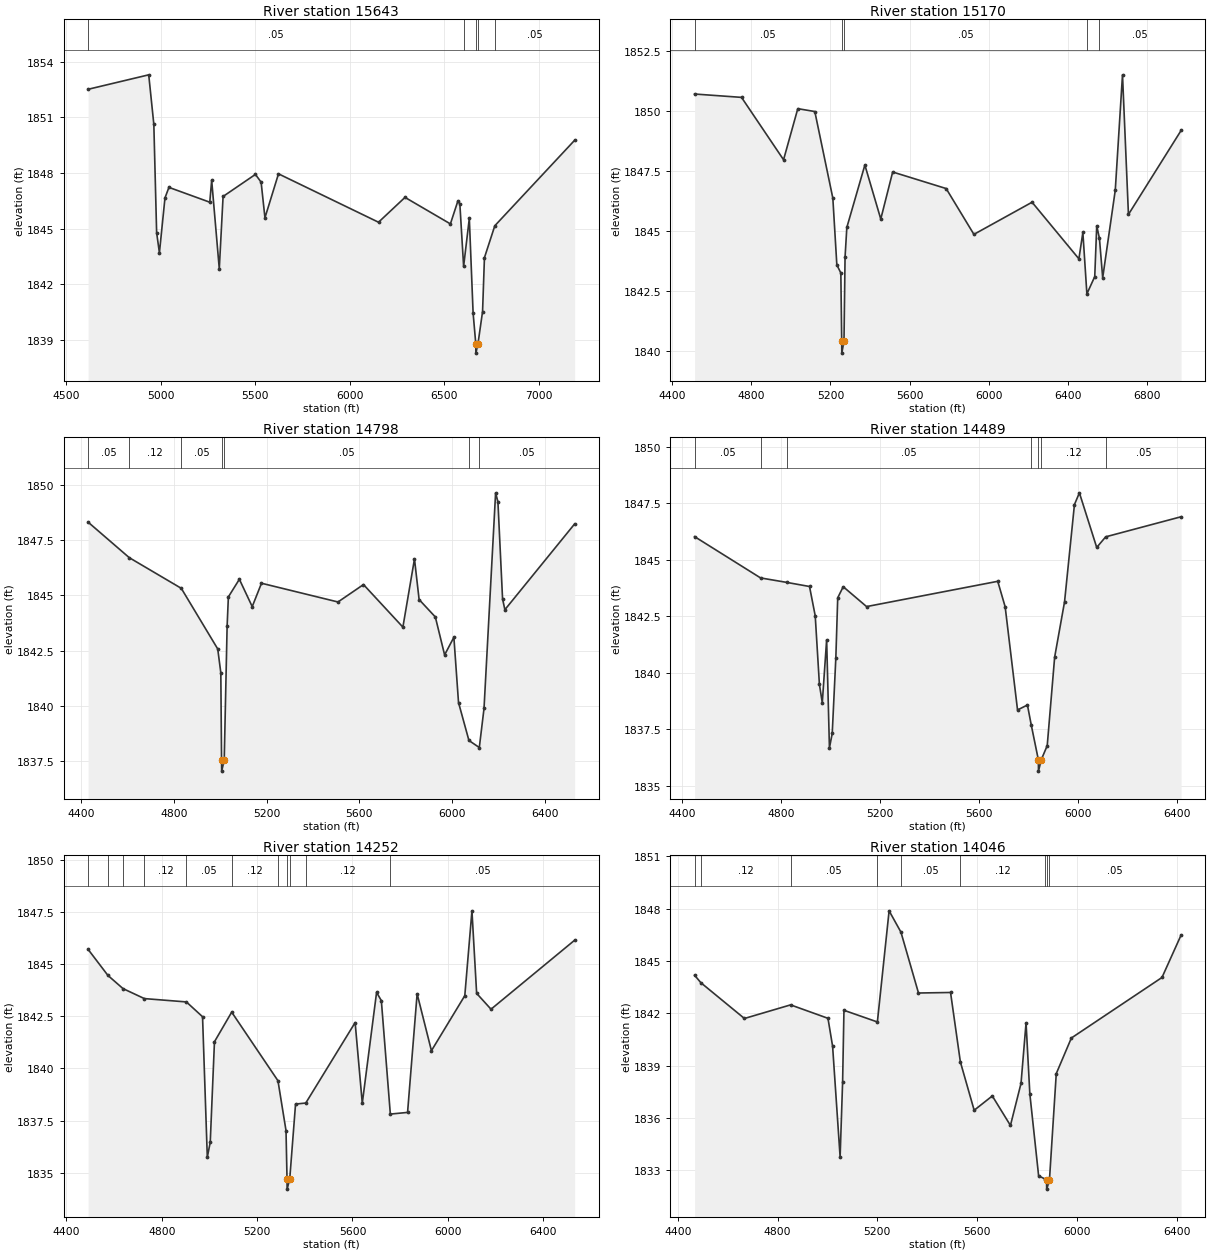
Type RM Length L Ch R = 1,15643,473,473,473
BEGIN DESCRIPTION:
Elm 01 78 15643.42
END DESCRIPTION:
XS GIS Cut Line= 5
      1591814.31      6803292.96      1592126.85      6803516.95
      1592210.03      6803577.31      1592722.53      6803631.64
      1594291.71      6803645.01
#Sta/Elev= 30
  4616.5 1852.52  4936.9 1853.30  4963.9 1850.63  4978.7 1844.79  4993.4 1843.70
  5022.8 1846.66  5043.7 1847.23  5259.6 1846.43  5269.7 1847.61  5309.9 1842.84
  5330.0 1846.74  5501.0 1847.93  5531.1 1847.51  5551.3 1845.59  5622.9 1847.96
  6151.7 1845.35  6291.7 1846.69  6531.7 1845.26  6571.7 1846.51  6581.7 1846.33
  6601.6 1842.97  6631.7 1845.56  6651.7 1840.46  6665.9 1838.79  6666.4 1838.29
  6677.4 1838.79  6701.7 1840.53  6711.7 1843.44  6766.5 1845.16  7188.4 1849.77
#Mann=5,-1,0
  4616.5    0.05       0  6601.6    0.12       0  6665.9    0.05       0
  6677.4    0.12       0  6766.5    0.05       0
Bank Sta=6665.9,6677.4
Exp/Cntr=0.3,0.1

Type RM Length L Ch R = 1,15170,372,372,372
BEGIN DESCRIPTION:
Elm 01 78 15170.16
END DESCRIPTION:
XS GIS Cut Line= 5
      1591876.84      6804114.18      1592237.96      6803789.51
      1592269.21      6803744.38      1592613.54      6803693.63
      1594180.74      6803730.94
#Sta/Elev= 30
  4514.0 1850.72  4751.0 1850.58  4963.2 1847.98  5035.1 1850.11  5121.0 1849.99
  5212.0 1846.38  5232.2 1843.60  5252.4 1843.26  5256.8 1840.42  5257.3 1839.92
  5268.3 1840.42  5273.7 1843.92  5282.7 1845.16  5373.7 1847.76  5454.0 1845.51
  5514.1 1847.47  5784.1 1846.78  5924.2 1844.87  6217.8 1846.21  6454.3 1843.85
  6474.3 1844.95  6494.6 1842.39  6534.3 1843.11  6544.3 1845.23  6558.0 1844.70
  6574.4 1843.06  6637.9 1846.71  6674.4 1851.52  6704.4 1845.70  6970.2 1849.20
#Mann=5,-1,0
  4514.0    0.05       0  5256.8    0.05       0  5268.3    0.05       0
  6494.6    0.12       0  6558.0    0.05       0
Bank Sta=5256.8,5268.3
Exp/Cntr=0.3,0.1

Type RM Length L Ch R = 1,14798,309,309,309
BEGIN DESCRIPTION:
Elm 01 78 14798.44
END DESCRIPTION:
XS GIS Cut Line= 4
      1592014.71      6804210.13      1592523.96      6803955.72
      1592613.09      6803917.95      1594045.92      6803913.25
#Sta/Elev= 30
  4430.3 1848.32  4607.8 1846.71  4832.2 1845.32  4989.5 1842.57  5002.8 1841.49
  5006.0 1837.53  5006.5 1837.03  5017.5 1837.53  5030.0 1843.60  5035.4 1844.93
  5082.8 1845.73  5138.3 1844.49  5178.3 1845.55  5508.3 1844.70  5618.3 1845.49
  5788.3 1843.56  5838.3 1846.65  5858.3 1844.81  5928.3 1844.02  5968.3 1842.30
  6008.3 1843.10  6028.3 1840.14  6073.2 1838.42  6118.0 1838.10  6138.3 1839.87
  6188.3 1849.65  6198.3 1849.24  6218.3 1844.84  6228.3 1844.35  6529.2 1848.24
#Mann=7,-1,0
  4430.3    0.05       0  4607.8    0.12       0  4832.2    0.05       0
  5006.0    0.05       0  5017.5    0.05       0  6073.2    0.12       0
  6118.0    0.05       0
Bank Sta=5006,5017.5
Exp/Cntr=0.3,0.1

Type RM Length L Ch R = 1,14489,237,237,237
BEGIN DESCRIPTION:
Elm 01 78 14488.93
END DESCRIPTION:
XS GIS Cut Line= 5
      1592102.15      6804285.58      1592544.53      6804208.86
      1592633.76      6804168.19      1592689.05      6804139.94
      1594045.95      6804118.98
#Sta/Elev= 30
  4451.5 1846.03  4718.2 1844.20  4824.8 1844.00  4916.0 1843.82  4939.1 1842.52
  4956.0 1839.48  4967.6 1838.67  4985.2 1841.46  4996.5 1836.67  5007.8 1837.31
  5022.4 1840.66  5030.0 1843.32  5052.2 1843.81  5146.6 1842.93  5676.7 1844.05
  5706.7 1842.92  5756.7 1838.35  5796.7 1838.57  5812.4 1837.67  5840.9 1836.14
  5841.4 1835.64  5852.4 1836.14  5876.7 1836.77  5906.7 1840.69  5946.7 1843.14
  5986.7 1847.45  6006.7 1847.97  6076.7 1845.55  6112.9 1846.02  6417.7 1846.91
#Mann=7,-1,0
  4451.5    0.05       0  4718.2    0.12       0  4824.8    0.05       0
  5812.4    0.12       0  5840.9    0.05       0  5852.4    0.12       0
  6112.9    0.05       0
Bank Sta=5840.9,5852.4
Exp/Cntr=0.3,0.1

Type RM Length L Ch R = 1,14252,206,206,206
BEGIN DESCRIPTION:
Elm 01 78 14252.09
END DESCRIPTION:
XS GIS Cut Line= 5
      1592110.84      6804322.46      1592460.29      6804387.04
      1592614.67      6804385.21      1592690.90      6804390.09
      1594145.76      6804366.38
#Sta/Elev= 30
  4491.0 1845.71  4574.2 1844.46  4637.3 1843.83  4727.0 1843.35  4903.3 1843.19
  4971.1 1842.48  4991.1 1835.74  5003.4 1836.46  5021.1 1841.28  5093.4 1842.70
  5287.5 1839.41  5321.3 1837.02  5325.5 1834.71  5326.0 1834.21  5337.0 1834.71
  5361.3 1838.29  5404.2 1838.34  5611.3 1842.20  5641.3 1838.33  5701.3 1843.65
  5721.3 1843.25  5759.0 1837.81  5831.3 1837.89  5871.4 1843.58  5931.4 1840.85
  6071.4 1843.49  6101.4 1847.56  6121.1 1843.60  6181.4 1842.84  6532.2 1846.15
#Mann=11,-1,0
  4491.0    0.05       0  4574.2    0.12       0  4637.3    0.05       0
  4727.0    0.12       0  4903.3    0.05       0  5093.4    0.12       0
  5287.5    0.05       0  5325.5    0.05       0  5337.0    0.05       0
  5404.2    0.12       0  5759.0    0.05       0
Bank Sta=5325.5,5337
Exp/Cntr=0.3,0.1

Type RM Length L Ch R = 1,14046,1059,1059,1059
BEGIN DESCRIPTION:
Elm 01 78 14045.75
END DESCRIPTION:
XS GIS Cut Line= 6
      1592163.40      6804392.47      1592583.92      6804583.62
      1592652.86      6804577.92      1592764.06      6804569.86
      1592968.06      6804589.39      1594060.94      6804441.94
#Sta/Elev= 30
  4467.3 1844.18  4492.5 1843.75  4667.1 1841.70  4852.2 1842.48  5002.0 1841.71
  5020.6 1840.11  5050.7 1833.76  5060.7 1838.06  5066.1 1842.17  5200.1 1841.50
  5247.1 1847.87  5294.5 1846.65  5364.9 1843.16  5493.4 1843.19  5532.8 1839.21
  5588.1 1836.44  5660.8 1837.26  5733.5 1835.57  5775.9 1837.98  5796.1 1841.45
  5811.3 1837.37  5846.5 1832.68  5873.8 1832.49  5878.3 1832.42  5878.8 1831.92
  5889.8 1832.42  5917.2 1838.54  5977.7 1840.58  6341.0 1844.05  6417.6 1846.48
#Mann=9,-1,0
  4467.3    0.05       0  4492.5    0.12       0  4852.2    0.05       0
  5200.1    0.12       0  5294.5    0.05       0  5532.8    0.12       0
  5873.8    0.05       0  5878.3    0.05       0  5889.8    0.05       0
Bank Sta=5878.3,5889.8
Exp/Cntr=0.3,0.1

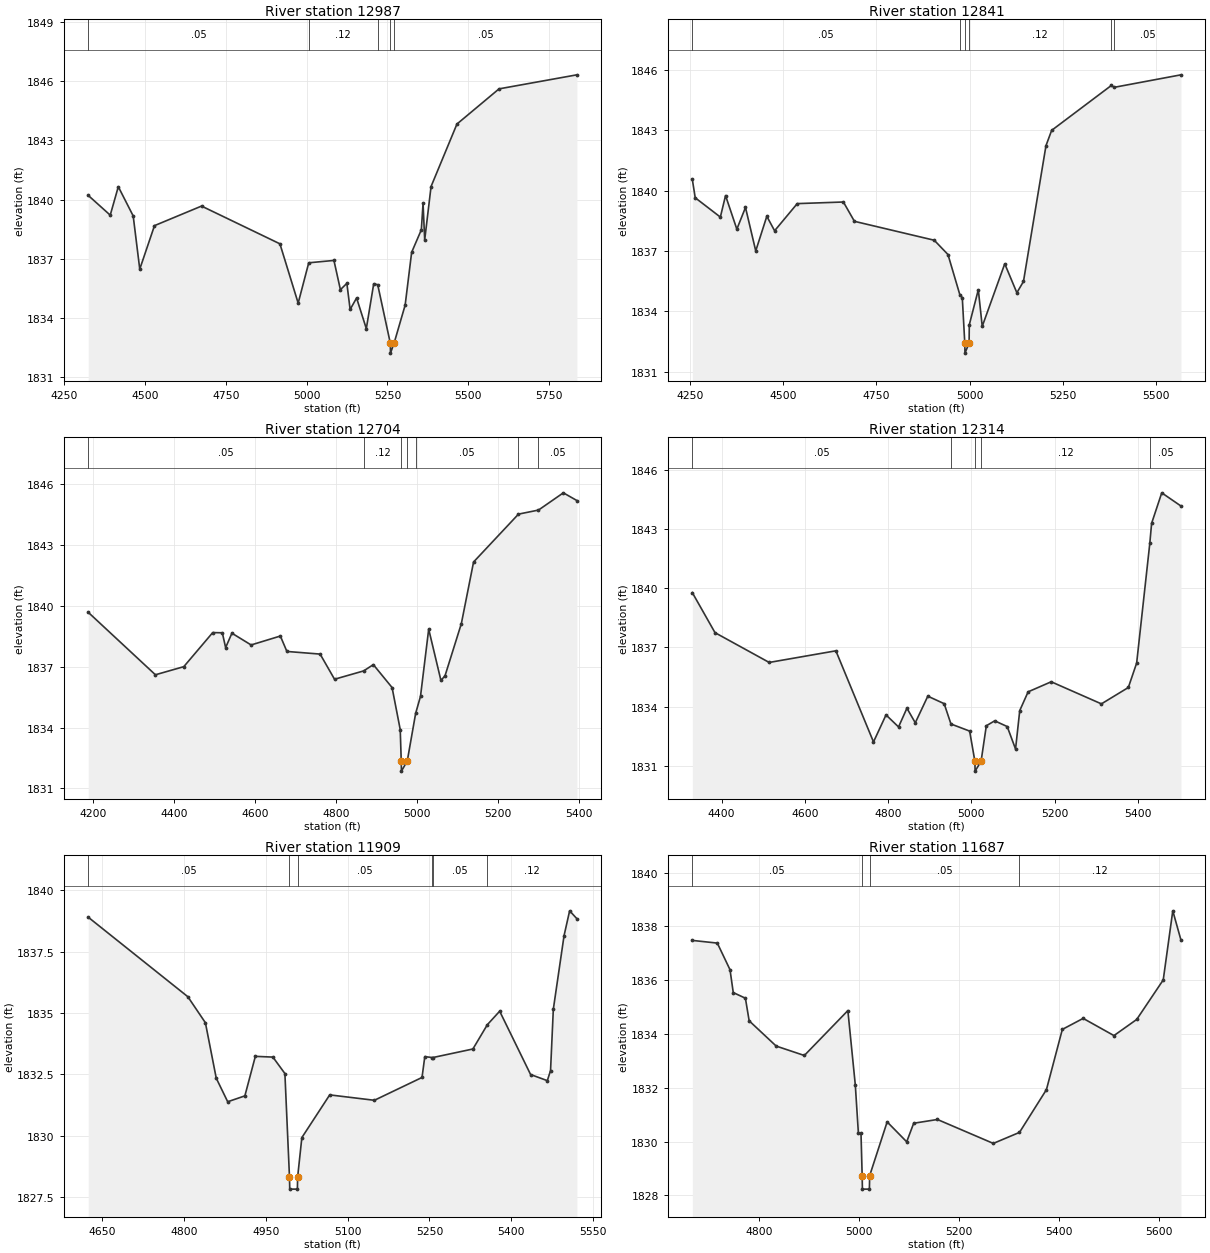
Type RM Length L Ch R = 1,12987,146,146,146
BEGIN DESCRIPTION:
Elm 01 78 13193.04
END DESCRIPTION:
XS GIS Cut Line= 6
      1592638.04      6805059.56      1592898.90      6805012.25
      1592980.93      6804986.20      1593096.09      6804799.90
      1593232.81      6804702.24      1594005.38      6804652.33
#Sta/Elev= 30
  4323.8 1840.21  4391.9 1839.21  4416.9 1840.65  4463.0 1839.17  4483.3 1836.48
  4528.9 1838.68  4674.5 1839.67  4917.1 1837.76  4973.6 1834.76  5006.3 1836.80
  5084.3 1836.92  5104.3 1835.44  5124.3 1835.76  5134.4 1834.44  5154.4 1835.02
  5184.5 1833.47  5207.4 1835.74  5219.8 1835.69  5258.8 1832.73  5259.3 1832.23
  5270.4 1832.73  5304.7 1834.66  5324.8 1837.33  5354.8 1838.47  5360.1 1839.81
  5365.2 1837.96  5384.9 1840.66  5465.0 1843.82  5595.3 1845.60  5836.2 1846.31
#Mann=5,-1,0
  4323.8    0.05       0  5006.3    0.12       0  5219.8    0.05       0
  5258.8    0.05       0  5270.4    0.05       0
Bank Sta=5258.8,5270.4
Exp/Cntr=0.3,0.1

Type RM Length L Ch R = 1,12841,137,137,137
BEGIN DESCRIPTION:
Elm 01 78 14015.336
END DESCRIPTION:
XS GIS Cut Line= 5
      1592637.03      6805064.99      1592992.98      6805008.56
      1593240.65      6804833.30      1593311.15      6804795.91
      1593875.18      6804736.96
#Sta/Elev= 30
  4256.4 1840.56  4264.2 1839.65  4331.6 1838.69  4345.5 1839.76  4375.8 1838.09
  4399.0 1839.17  4426.5 1837.01  4456.2 1838.73  4477.1 1838.01  4537.8 1839.36
  4661.6 1839.44  4691.2 1838.48  4905.3 1837.54  4942.1 1836.83  4974.0 1834.83
  4980.5 1834.69  4987.2 1832.43  4987.7 1831.93  4998.8 1832.43  4999.3 1833.34
  5023.5 1835.08  5034.0 1833.26  5094.4 1836.37  5126.9 1834.93  5144.6 1835.49
  5205.0 1842.24  5220.2 1843.00  5380.2 1845.23  5388.3 1845.14  5567.1 1845.76
#Mann=6,-1,0
  4256.4    0.05       0  4974.0    0.12       0  4987.2    0.05       0
  4998.8    0.12       0  5380.2    0.12       0  5388.3    0.05       0
Bank Sta=4987.2,4998.8
Exp/Cntr=0.3,0.1

Type RM Length L Ch R = 1,12704,390,390,390
BEGIN DESCRIPTION:
Elm 01 78 10297.259
END DESCRIPTION:
XS GIS Cut Line= 6
      1592639.25      6805078.00      1592936.55      6805064.98
      1593049.40      6805017.24      1593303.31      6804880.52
      1593406.93      6804872.88      1593798.16      6804824.54
#Sta/Elev= 30
  4187.6 1839.68  4353.5 1836.60  4423.6 1837.00  4495.0 1838.68  4518.7 1838.67
  4526.9 1837.94  4542.4 1838.65  4589.8 1838.07  4662.0 1838.51  4678.2 1837.75
  4760.2 1837.62  4795.8 1836.38  4867.6 1836.79  4891.6 1837.10  4937.9 1835.97
  4958.0 1833.90  4960.5 1832.35  4961.0 1831.85  4975.4 1832.35  4996.1 1834.70
  5008.1 1835.54  5028.3 1838.85  5058.5 1836.32  5068.6 1836.55  5108.9 1839.12
  5139.1 1842.16  5250.0 1844.52  5299.4 1844.72  5360.8 1845.57  5394.2 1845.19
#Mann=7,-1,0
  4187.6    0.05       0  4867.6    0.12       0  4960.5    0.05       0
  4975.4    0.12       0  4996.1    0.05       0  5250.0    0.12       0
  5299.4    0.05       0
Bank Sta=4960.5,4975.4
Exp/Cntr=0.3,0.1

Type RM Length L Ch R = 1,12314,405,405,405
BEGIN DESCRIPTION:
Elm 01 78 12314.4
END DESCRIPTION:
XS GIS Cut Line= 4
      1592630.56      6805091.02      1592966.78      6805107.91
      1593300.84      6805138.78      1593801.09      6805097.21
#Sta/Elev= 30
  4329.7 1839.78  4384.2 1837.75  4514.4 1836.24  4674.6 1836.83  4765.0 1832.21
  4795.1 1833.58  4825.2 1832.97  4845.3 1833.92  4865.4 1833.18  4895.5 1834.53
  4934.8 1834.15  4951.1 1833.12  4996.0 1832.76  5008.6 1831.23  5009.1 1830.73
  5023.5 1831.23  5036.1 1833.03  5056.2 1833.28  5086.3 1832.99  5106.3 1831.85
  5116.4 1833.80  5136.5 1834.75  5192.0 1835.26  5312.6 1834.14  5377.3 1834.97
  5397.3 1836.21  5429.0 1842.30  5433.2 1843.29  5457.6 1844.84  5503.8 1844.17
#Mann=5,-1,0
  4329.7    0.05       0  4951.1    0.12       0  5008.6    0.07       0
  5023.5    0.12       0  5429.0    0.05       0
Bank Sta=5008.6,5023.5
Exp/Cntr=0.3,0.1

Type RM Length L Ch R = 1,11909,222,222,222
BEGIN DESCRIPTION:
Elm 01 78 11909.14
END DESCRIPTION:
XS GIS Cut Line= 3
      1592621.18      6805149.21      1592977.92      6805262.48
      1593487.98      6805373.08
#Sta/Elev= 30
  4624.1 1838.90  4806.8 1835.66  4839.0 1834.60  4858.9 1832.34  4879.9 1831.38
  4911.4 1831.62  4930.6 1833.23  4962.8 1833.20  4984.8 1832.53  4993.2 1828.32
  4993.7 1827.82  5007.7 1827.82  5008.2 1828.32  5015.9 1829.92  5067.0 1831.66
  5148.9 1831.44  5236.3 1832.37  5241.4 1833.22  5255.5 1833.18  5255.8 1833.18
  5329.6 1833.53  5356.1 1834.52  5378.7 1835.07  5435.4 1832.49  5466.1 1832.24
  5472.0 1832.65  5477.1 1835.15  5496.8 1838.15  5507.0 1839.16  5520.3 1838.84
#Mann=6,-1,0
  4624.1    0.05       0  4993.2    0.05       0  5008.2    0.05       0
  5255.5    0.12       0  5255.8    0.05       0  5356.1    0.12       0
Bank Sta=4993.2,5008.2
Exp/Cntr=0.3,0.1

Type RM Length L Ch R = 1,11687,250,250,250
BEGIN DESCRIPTION:
Elm 01 78 11686.66
END DESCRIPTION:
XS GIS Cut Line= 3
      1592507.91      6805308.07      1592821.67      6805420.03
      1593428.44      6805637.48
#Sta/Elev= 30
  4666.2 1837.48  4716.2 1837.38  4741.6 1836.39  4748.1 1835.54  4772.4 1835.33
  4779.9 1834.49  4834.0 1833.55  4890.3 1833.20  4977.4 1834.87  4992.3 1832.10
  4998.5 1830.30  5003.7 1830.30  5006.0 1828.73  5006.5 1828.23  5020.5 1828.23
  5021.0 1828.73  5056.0 1830.73  5095.1 1829.99  5109.1 1830.68  5156.6 1830.82
  5268.4 1829.93  5320.8 1830.34  5374.7 1831.93  5406.5 1834.17  5448.2 1834.58
  5509.8 1833.94  5555.3 1834.54  5608.4 1836.01  5627.5 1838.58  5643.9 1837.49
#Mann=4,-1,0
  4666.2    0.05       0  5006.0    0.03       0  5021.0    0.05       0
  5320.8    0.12       0
Bank Sta=5006,5021
Exp/Cntr=0.3,0.1

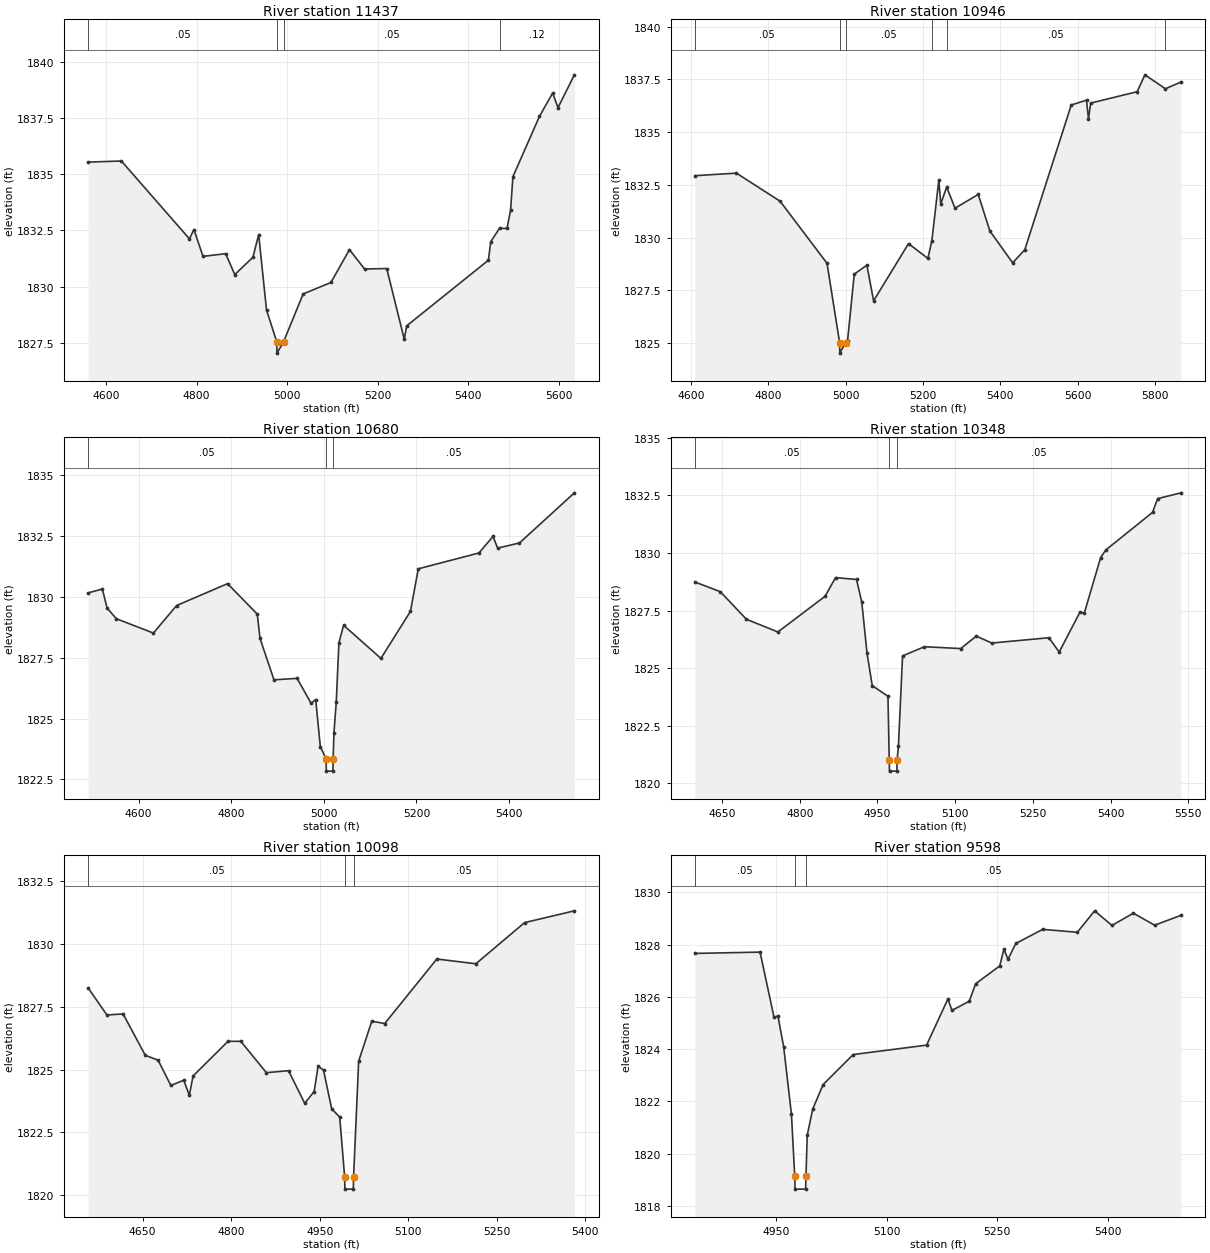
Type RM Length L Ch R = 1,11437,491,491,491
BEGIN DESCRIPTION:
Elm 01 78 11437.3
END DESCRIPTION:
XS GIS Cut Line= 3
      1592321.66      6805559.36      1592760.91      6805587.13
      1593380.37      6805722.48
#Sta/Elev= 30
  4560.3 1835.53  4633.8 1835.58  4784.1 1832.12  4794.1 1832.53  4814.1 1831.34
  4864.2 1831.46  4884.3 1830.53  4924.4 1831.30  4937.1 1832.31  4954.4 1828.96
  4977.0 1827.54  4977.5 1827.04  4992.0 1827.54  5035.3 1829.67  5096.7 1830.18
  5137.7 1831.64  5171.0 1830.78  5220.0 1830.80  5258.8 1827.65  5263.9 1828.25
  5444.6 1831.17  5449.7 1831.99  5469.1 1832.59  5485.7 1832.58  5493.6 1833.40
  5498.7 1834.88  5557.3 1837.56  5586.5 1838.60  5598.3 1837.95  5634.5 1839.41
#Mann=4,-1,0
  4560.3    0.05       0  4977.0    0.03       0  4992.0    0.05       0
  5469.1    0.12       0
Bank Sta=4977,4992
Exp/Cntr=0.3,0.1

Type RM Length L Ch R = 1,10946,266,266,266
BEGIN DESCRIPTION:
Elm 01 78 10946.32
END DESCRIPTION:
XS GIS Cut Line= 3
      1592196.64      6805908.31      1592585.56      6805960.40
      1593448.39      6806005.54
#Sta/Elev= 30
  4610.4 1832.94  4717.9 1833.06  4830.7 1831.73  4951.9 1828.79  4984.5 1825.03
  4985.0 1824.53  4999.7 1825.03  5005.0 1825.11  5022.3 1828.27  5054.9 1828.70
  5072.3 1827.01  5162.5 1829.72  5212.5 1829.02  5222.8 1829.85  5240.8 1832.73
  5245.8 1831.61  5261.2 1832.40  5282.6 1831.40  5342.7 1832.05  5372.7 1830.32
  5431.6 1828.81  5462.9 1829.43  5583.0 1836.29  5622.4 1836.52  5627.5 1835.63
  5633.1 1836.38  5753.3 1836.92  5773.3 1837.72  5826.3 1837.06  5866.8 1837.38
#Mann=6,-1,0
  4610.4    0.05       0  4984.5    0.03       0  4999.7    0.05       0
  5222.8    0.12       0  5261.2    0.05       0  5826.3    0.12       0
Bank Sta=4984.5,4999.7
Exp/Cntr=0.3,0.1

Type RM Length L Ch R = 1,10680,332,332,332
BEGIN DESCRIPTION:
Elm 01 78 10679.64
END DESCRIPTION:
XS GIS Cut Line= 3
      1591984.19      6806175.68      1592494.59      6806199.98
      1593029.35      6806267.70
#Sta/Elev= 30
  4491.0 1830.16  4521.8 1830.32  4531.9 1829.54  4551.9 1829.10  4632.0 1828.51
  4682.0 1829.64  4792.1 1830.54  4856.2 1829.29  4862.2 1828.29  4892.3 1826.59
  4942.3 1826.65  4972.3 1825.63  4982.4 1825.78  4992.4 1823.85  5004.9 1823.34
  5005.4 1822.84  5019.6 1822.84  5020.1 1823.34  5021.8 1824.40  5026.8 1825.67
  5032.6 1828.11  5042.7 1828.83  5123.3 1827.47  5187.0 1829.40  5204.0 1831.15
  5335.0 1831.80  5365.3 1832.48  5375.3 1832.00  5422.4 1832.21  5541.0 1834.27
#Mann=3,-1,0
  4491.0    0.05       0  5004.9    0.05       0  5020.1    0.05       0
Bank Sta=5004.9,5020.1
Exp/Cntr=0.3,0.1

Type RM Length L Ch R = 1,10348,250,250,250
BEGIN DESCRIPTION:
Elm 01 78 10348.49
END DESCRIPTION:
XS GIS Cut Line= 3
      1591956.41      6806359.71      1592355.70      6806420.47
      1592890.17      6806439.56
#Sta/Elev= 30
  4597.4 1828.74  4646.5 1828.32  4697.1 1827.12  4757.8 1826.57  4848.9 1828.12
  4869.1 1828.93  4909.5 1828.85  4919.7 1827.86  4929.8 1825.65  4939.9 1824.24
  4970.2 1823.78  4972.7 1821.03  4973.2 1820.53  4987.4 1820.53  4987.9 1821.03
  4990.5 1821.64  4998.4 1825.53  5040.6 1825.93  5110.7 1825.85  5140.7 1826.39
  5170.7 1826.09  5280.8 1826.32  5300.8 1825.70  5340.8 1827.43  5349.1 1827.38
  5380.8 1829.80  5390.8 1830.13  5480.9 1831.76  5490.9 1832.36  5536.1 1832.61
#Mann=3,-1,0
  4597.4    0.05       0  4972.7    0.03       0  4987.9    0.05       0
Bank Sta=4972.7,4987.9
Exp/Cntr=0.3,0.1

Type RM Length L Ch R = 1,10098,500,500,500
BEGIN DESCRIPTION:
Elm 01 78 10098.47
END DESCRIPTION:
XS GIS Cut Line= 3
      1591945.67      6806445.36      1592334.17      6806664.57
      1592668.39      6806840.35
#Sta/Elev= 30
  4557.6 1828.26  4589.5 1827.18  4616.9 1827.22  4654.5 1825.57  4676.1 1825.38
  4697.8 1824.37  4719.5 1824.58  4729.1 1823.98  4735.4 1824.75  4794.6 1826.13
  4816.3 1826.13  4859.6 1824.88  4897.1 1824.96  4924.5 1823.66  4940.5 1824.13
  4947.2 1825.14  4956.4 1824.98  4970.2 1823.44  4983.8 1823.11  4992.1 1820.74
  4992.6 1820.24  5006.8 1820.24  5007.3 1820.74  5015.9 1825.34  5038.1 1826.93
  5060.1 1826.84  5148.3 1829.41  5214.4 1829.22  5296.9 1830.86  5381.3 1831.33
#Mann=3,-1,0
  4557.6    0.05       0  4992.1    0.03       0  5007.3    0.05       0
Bank Sta=4992.1,5007.3
Exp/Cntr=0.3,0.1

Type RM Length L Ch R = 1,9598,845,845,845
BEGIN DESCRIPTION:
Elm 01 78 9598.21
END DESCRIPTION:
XS GIS Cut Line= 3
      1591772.08      6806664.55      1591924.01      6806720.99
      1592380.95      6806918.06
#Sta/Elev= 30
  4839.8 1827.66  4928.3 1827.71  4947.2 1825.22  4952.6 1825.26  4960.3 1824.09
  4970.9 1821.50  4975.3 1819.14  4975.8 1818.64  4990.1 1818.64  4990.6 1819.14
  4992.3 1820.70  4999.7 1821.70  5013.8 1822.64  5054.7 1823.79  5154.2 1824.15
  5183.2 1825.92  5188.6 1825.48  5212.1 1825.83  5220.8 1826.50  5253.4 1827.18
  5259.2 1827.83  5264.6 1827.43  5275.2 1828.04  5311.7 1828.58  5358.7 1828.47
  5382.2 1829.29  5405.7 1828.73  5434.7 1829.20  5463.6 1828.74  5499.5 1829.12
#Mann=3,-1,0
  4839.8    0.05       0  4975.3    0.05       0  4990.6    0.05       0
Bank Sta=4975.3,4990.6
Exp/Cntr=0.3,0.1

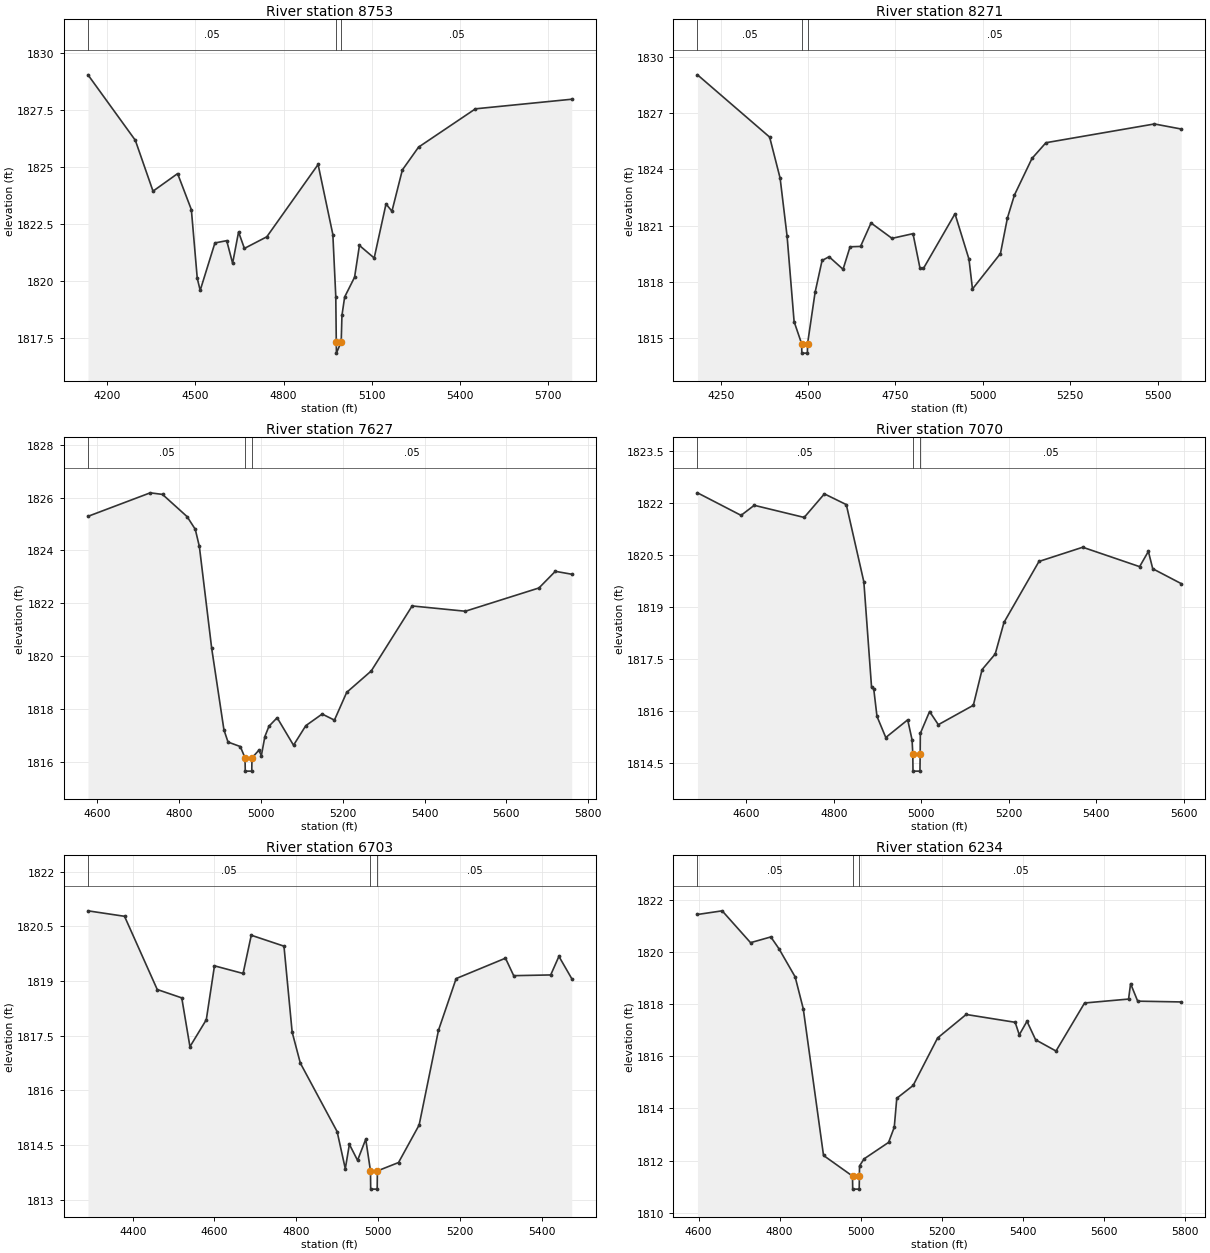
Type RM Length L Ch R = 1,8753,482,482,482
BEGIN DESCRIPTION:
Elm 01 78 8753.33
END DESCRIPTION:
XS GIS Cut Line= 3
      1590744.33      6807013.29      1591605.86      6807097.93
      1592383.26      6807193.21
#Sta/Elev= 30
  4133.5 1829.03  4294.9 1826.16  4355.2 1823.93  4439.0 1824.70  4485.9 1823.12
  4506.0 1820.11  4516.0 1819.58  4566.2 1821.66  4606.4 1821.76  4626.5 1820.77
  4646.8 1822.14  4666.7 1821.42  4743.1 1821.93  4917.9 1825.10  4968.2 1822.03
  4978.2 1819.31  4979.9 1817.33  4980.4 1816.83  4996.7 1817.33  4999.2 1818.48
  5008.4 1819.29  5042.3 1820.16  5058.8 1821.55  5109.1 1821.00  5149.4 1823.37
  5169.6 1823.05  5205.1 1824.86  5260.3 1825.86  5454.3 1827.54  5782.4 1827.96
#Mann=3,-1,0
  4133.5    0.05       0  4979.9    0.03       0  4996.7    0.05       0
Bank Sta=4979.9,4996.7
Exp/Cntr=0.3,0.1

Type RM Length L Ch R = 1,8271,644,644,644
BEGIN DESCRIPTION:
Elm 01 78 8271.27
END DESCRIPTION:
XS GIS Cut Line= 3
      1590688.71      6807500.13      1591502.56      6807510.98
      1592071.63      6807489.34
#Sta/Elev= 30
  4183.8 1829.04  4390.1 1825.72  4420.1 1823.53  4440.1 1820.42  4460.1 1815.88
  4481.7 1814.70  4482.2 1814.20  4498.1 1814.20  4498.6 1814.70  4520.1 1817.44
  4540.1 1819.14  4560.1 1819.34  4600.1 1818.67  4620.1 1819.87  4650.1 1819.89
  4680.1 1821.14  4740.1 1820.32  4800.1 1820.57  4820.1 1818.73  4830.1 1818.72
  4920.2 1821.63  4960.2 1819.21  4970.2 1817.62  5050.2 1819.51  5070.2 1821.41
  5090.2 1822.63  5140.3 1824.58  5180.3 1825.42  5490.5 1826.42  5567.2 1826.15
#Mann=3,-1,0
  4183.8    0.05       0  4481.7    0.05       0  4498.6    0.05       0
Bank Sta=4481.7,4498.6
Exp/Cntr=0.3,0.1

Type RM Length L Ch R = 1,7627,557,557,557
BEGIN DESCRIPTION:
Elm 01 78 7626.83
END DESCRIPTION:
XS GIS Cut Line= 3
      1590732.90      6807990.11      1591156.47      6807972.75
      1591915.14      6807976.23
#Sta/Elev= 30
  4577.0 1825.29  4729.2 1826.18  4759.2 1826.12  4819.3 1825.28  4839.3 1824.80
  4849.3 1824.15  4879.4 1820.30  4909.4 1817.21  4919.4 1816.75  4949.4 1816.58
  4961.0 1816.15  4961.5 1815.65  4977.4 1815.65  4977.9 1816.15  4994.7 1816.44
  5000.9 1816.24  5009.5 1816.96  5019.5 1817.35  5039.5 1817.67  5079.5 1816.63
  5109.5 1817.37  5149.5 1817.81  5179.5 1817.58  5209.5 1818.63  5269.5 1819.44
  5369.5 1821.90  5499.5 1821.70  5679.5 1822.58  5719.5 1823.21  5759.6 1823.10
#Mann=3,-1,0
  4577.0    0.05       0  4961.0    0.05       0  4977.9    0.05       0
Bank Sta=4961,4977.9
Exp/Cntr=0.3,0.1

Type RM Length L Ch R = 1,7070,367,367,367
BEGIN DESCRIPTION:
Elm 01 78 7070.12
END DESCRIPTION:
XS GIS Cut Line= 3
      1590495.60      6808287.60      1591007.74      6808320.15
      1591600.06      6808320.15
#Sta/Elev= 30
  4488.6 1822.30  4588.2 1821.65  4618.3 1821.94  4732.4 1821.59  4778.6 1822.27
  4828.7 1821.96  4868.8 1819.73  4886.4 1816.69  4891.4 1816.64  4898.8 1815.85
  4918.9 1815.24  4969.0 1815.75  4979.0 1815.17  4980.6 1814.77  4981.1 1814.27
  4997.0 1814.27  4997.5 1814.77  4997.9 1815.36  5019.0 1815.99  5039.0 1815.61
  5119.0 1816.17  5139.0 1817.20  5169.0 1817.65  5189.0 1818.56  5269.0 1820.32
  5369.0 1820.73  5499.0 1820.17  5519.0 1820.61  5529.0 1820.11  5594.1 1819.68
#Mann=3,-1,0
  4488.6    0.05       0  4980.6    0.05       0  4997.5    0.05       0
Bank Sta=4980.6,4997.5
Exp/Cntr=0.3,0.1

Type RM Length L Ch R = 1,6703,469,469,469
BEGIN DESCRIPTION:
Elm 01 78 6703.39
END DESCRIPTION:
XS GIS Cut Line= 3
      1590495.56      6808606.61      1591205.22      6808608.78
      1591676.12      6808558.87
#Sta/Elev= 30
  4290.6 1820.93  4380.0 1820.78  4460.0 1818.77  4520.0 1818.54  4540.0 1817.20
  4580.0 1817.94  4600.0 1819.42  4670.0 1819.21  4690.0 1820.26  4770.0 1819.96
  4790.0 1817.60  4810.0 1816.75  4900.0 1814.87  4920.0 1813.85  4930.0 1814.52
  4950.0 1814.08  4970.0 1814.66  4981.6 1813.79  4982.1 1813.29  4998.0 1813.29
  4998.5 1813.79  5050.2 1814.02  5100.6 1815.05  5147.9 1817.65  5191.1 1819.07
  5311.8 1819.63  5331.9 1819.15  5422.4 1819.17  5442.5 1819.68  5473.8 1819.07
#Mann=3,-1,0
  4290.6    0.05       0  4981.6    0.05       0  4998.5    0.05       0
Bank Sta=4981.6,4998.5
Exp/Cntr=0.3,0.1

Type RM Length L Ch R = 1,6234,352,352,352
BEGIN DESCRIPTION:
Elm 01 78 6234.45
END DESCRIPTION:
XS GIS Cut Line= 3
      1590604.10      6808957.30      1591005.57      6808952.96
      1591791.63      6808857.68
#Sta/Elev= 30
  4597.5 1821.43  4658.4 1821.57  4728.4 1820.35  4778.4 1820.57  4798.4 1820.12
  4838.4 1819.04  4858.4 1817.82  4908.4 1812.20  4979.9 1811.41  4980.4 1810.91
  4996.4 1810.91  4996.9 1811.41  4997.2 1811.80  5008.5 1812.07  5068.9 1812.70
  5082.9 1813.28  5089.1 1814.39  5129.4 1814.88  5189.8 1816.70  5260.3 1817.60
  5381.2 1817.30  5391.3 1816.82  5410.3 1817.34  5431.6 1816.63  5481.9 1816.20
  5552.4 1818.04  5660.9 1818.19  5665.9 1818.78  5683.4 1818.11  5790.8 1818.08
#Mann=3,-1,0
  4597.5    0.05       0  4979.9    0.05       0  4996.9    0.05       0
Bank Sta=4979.9,4996.9
Exp/Cntr=0.3,0.1