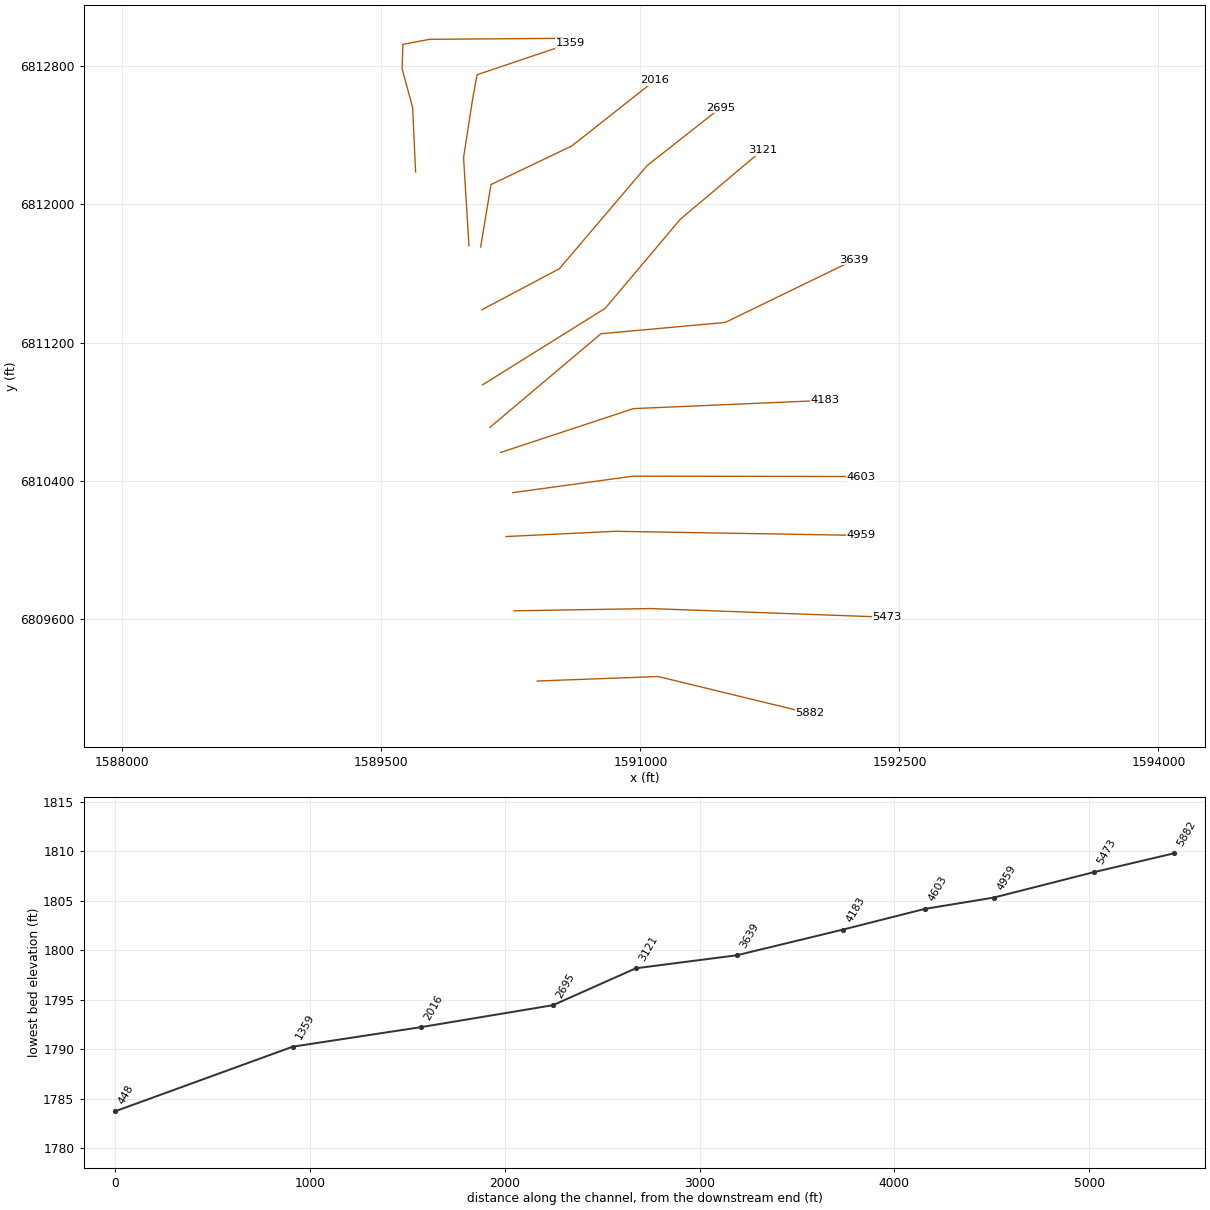
HEC-RAS study Elm 01 78.prj: Elm 01 78 Base Level Engineering

--- Elm 01 78.g01 (geometry) --- (continued)

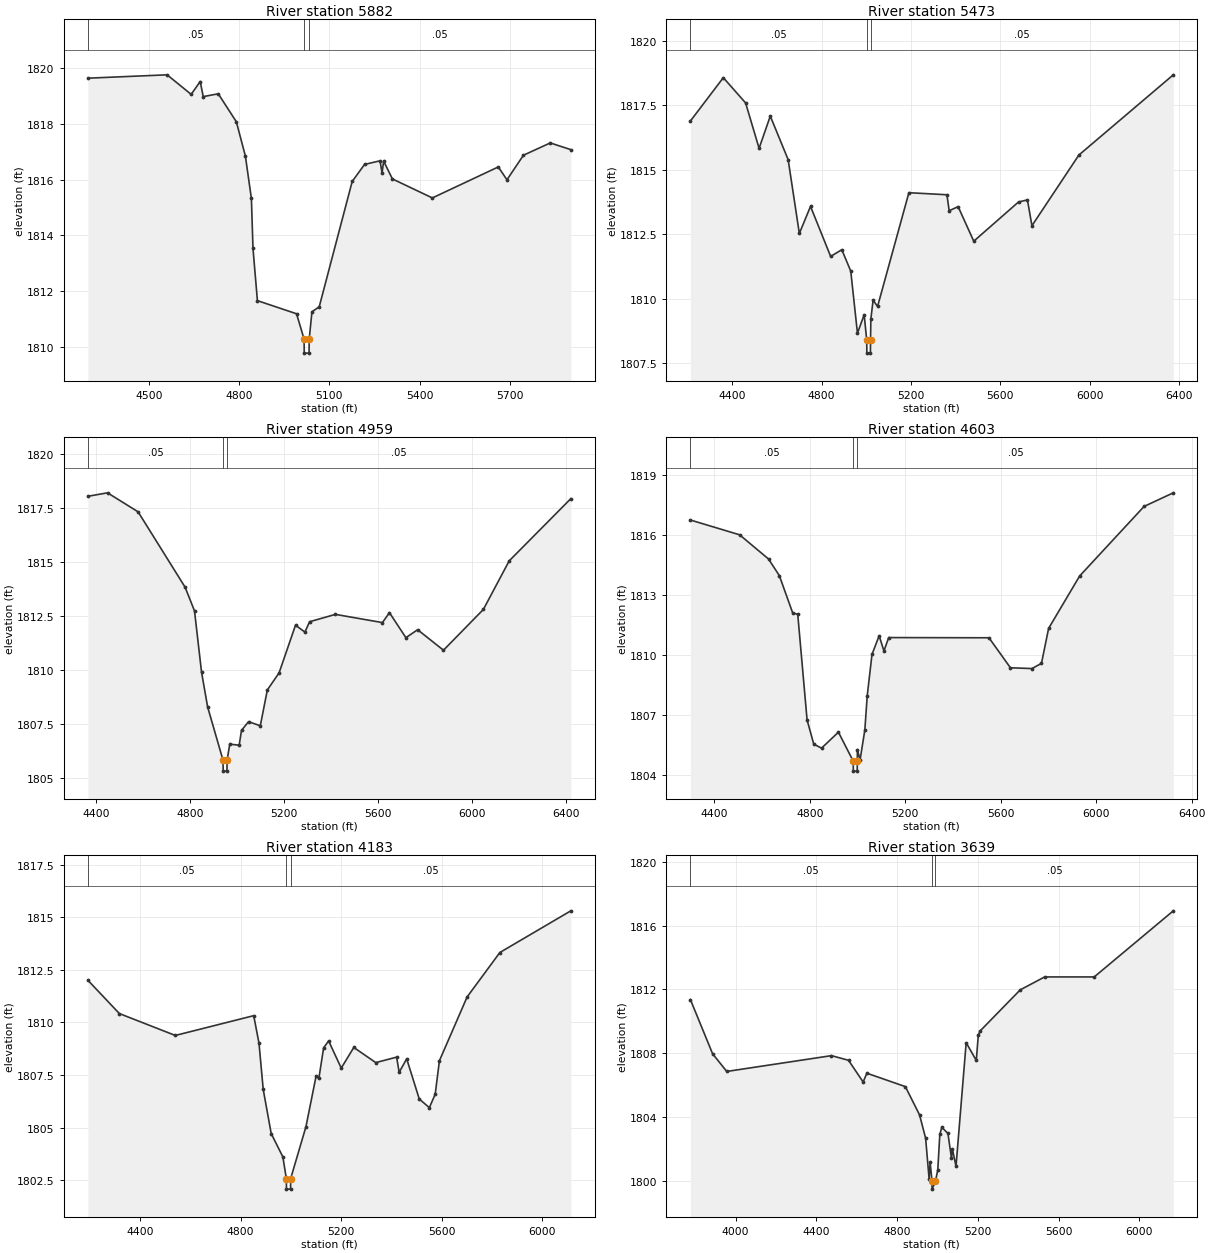
Type RM Length L Ch R = 1,5882,409,409,409
BEGIN DESCRIPTION:
Elm 01 78 5882.18
END DESCRIPTION:
XS GIS Cut Line= 3
      1590402.01      6809242.60      1591102.50      6809268.65
      1591981.33      6809055.44
#Sta/Elev= 30
  4297.3 1819.63  4560.5 1819.75  4640.5 1819.05  4670.5 1819.51  4680.6 1818.97
  4730.6 1819.07  4790.6 1818.07  4820.7 1816.84  4840.7 1815.32  4846.0 1813.53
  4860.7 1811.66  4990.8 1811.19  5015.9 1810.28  5016.4 1809.78  5032.4 1809.78
  5032.9 1810.28  5042.0 1811.26  5066.2 1811.44  5175.8 1815.93  5216.9 1816.54
  5268.4 1816.67  5275.1 1816.23  5280.3 1816.66  5309.5 1816.02  5442.3 1815.34
  5661.5 1816.45  5690.3 1815.99  5745.1 1816.87  5834.3 1817.31  5902.6 1817.07
#Mann=3,-1,0
  4297.3    0.05       0  5015.9    0.05       0  5032.9    0.05       0
Bank Sta=5015.9,5032.9
Exp/Cntr=0.3,0.1

Type RM Length L Ch R = 1,5473,514,514,514
BEGIN DESCRIPTION:
Elm 01 78 5472.95
END DESCRIPTION:
XS GIS Cut Line= 3
      1590267.79      6809648.85      1591057.71      6809661.87
      1592427.08      6809611.96
#Sta/Elev= 30
  4213.1 1816.89  4360.3 1818.57  4460.0 1817.59  4520.3 1815.83  4570.4 1817.08
  4650.4 1815.39  4700.4 1812.53  4750.4 1813.58  4840.4 1811.64  4890.4 1811.90
  4930.4 1811.07  4960.4 1808.66  4990.4 1809.38  5001.9 1808.39  5002.4 1807.89
  5018.4 1807.89  5018.9 1808.39  5020.4 1809.22  5030.4 1809.94  5050.4 1809.70
  5190.5 1814.11  5360.7 1814.03  5370.7 1813.41  5410.7 1813.57  5480.7 1812.23
  5680.9 1813.75  5720.9 1813.83  5740.9 1812.83  5951.0 1815.57  6373.4 1818.68
#Mann=3,-1,0
  4213.1    0.05       0  5001.9    0.05       0  5018.9    0.05       0
Bank Sta=5001.9,5018.9
Exp/Cntr=0.3,0.1

Type RM Length L Ch R = 1,4959,356,356,356
BEGIN DESCRIPTION:
Elm 01 78 4958.77
END DESCRIPTION:
XS GIS Cut Line= 3
      1590221.66      6810078.54      1590855.31      6810108.92
      1592277.33      6810085.05
#Sta/Elev= 30
  4365.9 1818.05  4449.3 1818.21  4579.5 1817.33  4779.7 1813.84  4819.8 1812.74
  4849.8 1809.90  4875.7 1808.29  4941.4 1805.82  4941.9 1805.32  4958.0 1805.32
  4958.5 1805.82  4969.9 1806.57  5010.0 1806.52  5020.0 1807.21  5050.0 1807.61
  5100.0 1807.42  5130.0 1809.08  5180.0 1809.87  5250.0 1812.08  5290.0 1811.76
  5310.0 1812.24  5420.0 1812.58  5620.1 1812.20  5650.1 1812.66  5720.1 1811.50
  5770.1 1811.87  5880.1 1810.92  6050.1 1812.81  6160.1 1815.06  6422.5 1817.94
#Mann=3,-1,0
  4365.9    0.05       0  4941.4    0.05       0  4958.5    0.05       0
Bank Sta=4941.4,4958.5
Exp/Cntr=0.3,0.1

Type RM Length L Ch R = 1,4603,420,420,420
BEGIN DESCRIPTION:
Elm 01 78 4603.4
END DESCRIPTION:
XS GIS Cut Line= 3
      1590260.69      6810332.45      1590957.30      6810427.93
      1592277.37      6810425.76
#Sta/Elev= 30
  4299.9 1816.73  4506.1 1815.99  4627.2 1814.78  4672.4 1813.95  4728.2 1812.09
  4749.6 1812.01  4788.7 1806.73  4816.7 1805.52  4849.3 1805.32  4920.0 1806.12
  4982.0 1804.67  4982.5 1804.17  4998.7 1804.17  4999.2 1804.67  4999.3 1805.25
  5010.7 1804.73  5030.7 1806.23  5040.7 1807.94  5060.7 1810.01  5090.7 1810.94
  5110.7 1810.18  5130.7 1810.85  5550.7 1810.84  5640.7 1809.34  5730.7 1809.30
  5770.7 1809.56  5800.7 1811.31  5930.7 1813.93  6200.7 1817.41  6323.1 1818.09
#Mann=3,-1,0
  4299.9    0.05       0  4982.0    0.05       0  4999.2    0.05       0
Bank Sta=4982,4999.2
Exp/Cntr=0.3,0.1

Type RM Length L Ch R = 1,4183,544,544,544
BEGIN DESCRIPTION:
Elm 01 78 4182.5
END DESCRIPTION:
XS GIS Cut Line= 3
      1590189.09      6810564.66      1590959.47      6810818.56
      1592066.80      6810866.30
#Sta/Elev= 30
  4193.3 1812.00  4318.2 1810.42  4540.6 1809.38  4852.3 1810.32  4873.4 1809.00
  4890.0 1806.82  4921.8 1804.72  4968.2 1803.61  4982.0 1802.58  4982.5 1802.08
  4998.7 1802.08  4999.2 1802.58  5060.0 1805.05  5100.1 1807.44  5111.3 1807.34
  5130.1 1808.79  5150.1 1809.12  5200.2 1807.83  5250.2 1808.81  5337.5 1808.09
  5420.4 1808.35  5430.4 1807.63  5460.4 1808.27  5510.4 1806.36  5550.5 1805.95
  5573.7 1806.59  5590.5 1808.18  5700.6 1811.21  5830.7 1813.32  6112.8 1815.30
#Mann=3,-1,0
  4193.3    0.05       0  4982.0    0.05       0  4999.2    0.05       0
Bank Sta=4982,4999.2
Exp/Cntr=0.3,0.1

Type RM Length L Ch R = 1,3639,518,518,518
BEGIN DESCRIPTION:
Mapping XS eaa8eac0
END DESCRIPTION:
XS GIS Cut Line= 4
      1590128.38      6810710.31      1590771.59      6811251.96
      1591490.34      6811317.06      1592237.71      6811679.03
#Sta/Elev= 30
  3775.9 1811.36  3885.7 1807.97  3955.9 1806.86  4474.8 1807.85  4559.4 1807.56
  4631.8 1806.20  4650.3 1806.75  4841.1 1805.91  4911.4 1804.14  4941.5 1802.68
  4958.7 1800.14  4963.8 1801.17  4973.1 1799.99  4973.6 1799.49  4990.3 1799.99
  5001.8 1800.70  5011.8 1802.92  5021.9 1803.36  5052.0 1802.98  5069.4 1801.45
  5074.4 1801.98  5092.1 1800.92  5142.4 1808.66  5192.6 1807.55  5202.6 1809.14
  5212.6 1809.41  5410.3 1811.97  5531.3 1812.78  5777.0 1812.78  6168.9 1816.92
#Mann=3,-1,0
  3775.9    0.05       0  4973.1    0.05       0  4990.3    0.05       0
Bank Sta=4973.1,4990.3
Exp/Cntr=0.3,0.1

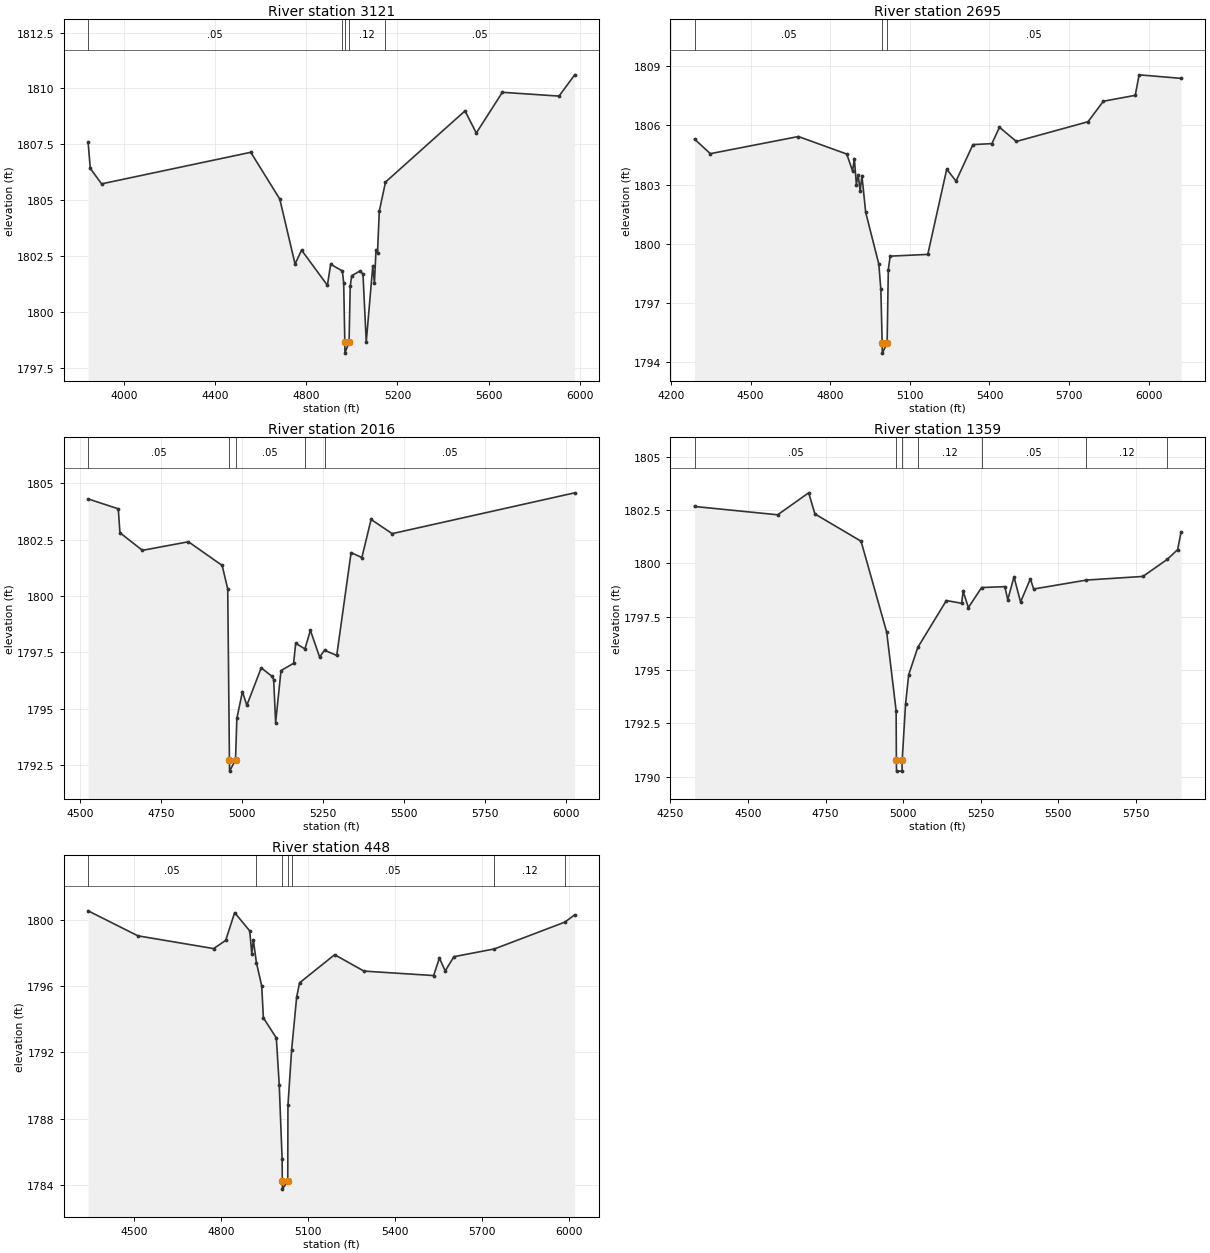
Type RM Length L Ch R = 1,3121,426,426,426
BEGIN DESCRIPTION:
Mapping XS 376bf2f1
END DESCRIPTION:
XS GIS Cut Line= 4
      1590084.99      6810955.98      1590795.89      6811398.66
      1591230.79      6811914.29      1591706.00      6812314.20
#Sta/Elev= 30
  3843.7 1807.59  3853.3 1806.43  3902.6 1805.74  4556.7 1807.15  4684.0 1805.06
  4750.9 1802.16  4779.5 1802.78  4892.7 1801.21  4907.0 1802.15  4958.3 1801.85
  4964.1 1801.32  4969.1 1798.68  4969.6 1798.18  4987.7 1798.68  4992.7 1801.16
  4999.3 1801.64  5034.4 1801.84  5048.7 1801.72  5063.0 1798.68  5091.6 1802.07
  5098.9 1801.32  5105.9 1802.80  5112.4 1802.67  5120.2 1804.52  5147.4 1805.82
  5496.0 1809.00  5545.4 1808.01  5659.8 1809.83  5908.2 1809.66  5976.8 1810.61
#Mann=5,-1,0
  3843.7    0.05       0  4958.3    0.12       0  4969.1    0.07       0
  4987.7    0.12       0  5147.4    0.05       0
Bank Sta=4969.1,4987.7
Exp/Cntr=0.3,0.1

Type RM Length L Ch R = 1,2695,679,679,679
BEGIN DESCRIPTION:
Mapping XS 612f6a92
END DESCRIPTION:
XS GIS Cut Line= 4
      1590082.37      6811390.86      1590530.27      6811627.83
      1591038.08      6812224.18      1591465.19      6812560.14
#Sta/Elev= 30
  4288.7 1805.31  4348.2 1804.57  4680.1 1805.44  4862.3 1804.55  4884.3 1803.69
  4890.9 1804.32  4898.6 1803.00  4905.1 1803.50  4912.8 1802.68  4919.4 1803.46
  4933.7 1801.59  4983.1 1798.97  4990.8 1797.68  4995.8 1794.95  4996.3 1794.45
  5014.4 1794.95  5018.9 1798.69  5025.9 1799.37  5167.6 1799.46  5239.0 1803.78
  5274.1 1803.18  5337.8 1805.03  5409.2 1805.08  5437.7 1805.91  5501.4 1805.19
  5771.4 1806.19  5829.2 1807.23  5949.4 1807.53  5963.9 1808.57  6122.1 1808.39
#Mann=3,-1,0
  4288.7    0.05       0  4995.8    0.03       0  5014.4    0.05       0
Bank Sta=4995.8,5014.4
Exp/Cntr=0.3,0.1

Type RM Length L Ch R = 1,2016,657,657,657
BEGIN DESCRIPTION:
Mapping XS a8dc2310
END DESCRIPTION:
XS GIS Cut Line= 4
      1590074.54      6811752.87      1590134.43      6812114.81
      1590603.18      6812338.77      1591084.96      6812718.98
#Sta/Elev= 30
  4525.8 1804.30  4618.8 1803.86  4623.9 1802.80  4693.2 1802.02  4835.1 1802.40
  4939.0 1801.35  4956.2 1800.31  4961.5 1792.73  4962.0 1792.23  4980.2 1792.73
  4984.4 1794.57  5001.5 1795.75  5015.2 1795.15  5059.5 1796.81  5092.2 1796.44
  5097.8 1796.29  5103.9 1794.38  5120.5 1796.69  5159.3 1797.01  5165.8 1797.90
  5194.1 1797.65  5211.2 1798.47  5239.4 1797.29  5254.8 1797.59  5292.3 1797.36
  5336.6 1801.92  5369.8 1801.70  5398.2 1803.39  5463.2 1802.76  6025.9 1804.57
#Mann=5,-1,0
  4525.8    0.05       0  4961.5    0.05       0  4980.2    0.05       0
  5194.1    0.12       0  5254.8    0.05       0
Bank Sta=4961.5,4980.2
Exp/Cntr=0.3,0.1

Type RM Length L Ch R = 1,1359,911,911,911
BEGIN DESCRIPTION:
Mapping XS 7f0075f1
END DESCRIPTION:
XS GIS Cut Line= 5
      1590006.83      6811760.65      1589975.58      6812271.06
      1590027.66      6812607.00      1590053.71      6812750.22
      1590595.38      6812932.77
#Sta/Elev= 30
  4327.5 1802.67  4595.4 1802.28  4695.5 1803.31  4715.6 1802.32  4864.4 1801.04
  4947.1 1796.77  4977.4 1793.09  4978.2 1790.76  4978.7 1790.26  4996.4 1790.26
  4996.9 1790.76  5007.8 1793.41  5017.9 1794.78  5047.2 1796.06  5139.4 1798.26
  5188.4 1798.13  5193.5 1798.69  5210.3 1797.93  5253.1 1798.87  5327.7 1798.91
  5337.3 1798.30  5357.4 1799.37  5378.5 1798.19  5410.2 1799.28  5420.7 1798.80
  5591.0 1799.22  5772.9 1799.39  5851.5 1800.19  5885.0 1800.65  5896.0 1801.48
#Mann=7,-1,0
  4327.5    0.05       0  4978.2    0.03       0  4996.9    0.05       0
  5047.2    0.12       0  5253.1    0.05       0  5591.0    0.12       0
  5851.5    0.05       0
Bank Sta=4978.2,4996.9
Exp/Cntr=0.3,0.1

Type RM Length L Ch R = 1,448,0,0,0
BEGIN DESCRIPTION:
Elm 01 78 5549.134
END DESCRIPTION:
XS GIS Cut Line= 6
      1589697.80      6812188.16      1589680.44      6812561.42
      1589619.68      6812784.95      1589624.02      6812926.01
      1589779.67      6812955.38      1590551.02      6812960.98
#Sta/Elev= 30
  4341.7 1800.55  4513.2 1799.04  4774.0 1798.27  4815.5 1798.76  4846.5 1800.44
  4898.4 1799.34  4905.6 1797.95  4910.8 1798.80  4921.5 1797.41  4939.8 1796.01
  4945.4 1794.09  4990.1 1792.87  5000.1 1790.04  5010.1 1785.53  5010.7 1784.24
  5011.2 1783.74  5029.4 1784.24  5030.1 1788.80  5042.9 1792.17  5060.1 1795.34
  5070.1 1796.20  5190.9 1797.90  5291.9 1796.91  5531.9 1796.64  5551.9 1797.70
  5571.9 1796.92  5601.9 1797.78  5741.5 1798.25  5984.3 1799.87  6017.9 1800.31
#Mann=7,-1,0
  4341.7    0.05       0  4921.5    0.12       0  5010.7    0.07       0
  5029.4    0.12       0  5042.9    0.05       0  5741.5    0.12       0
  5984.3    0.05       0
Bank Sta=5010.7,5029.4
Exp/Cntr=0.3,0.1

Chan Stop Cuts=-1