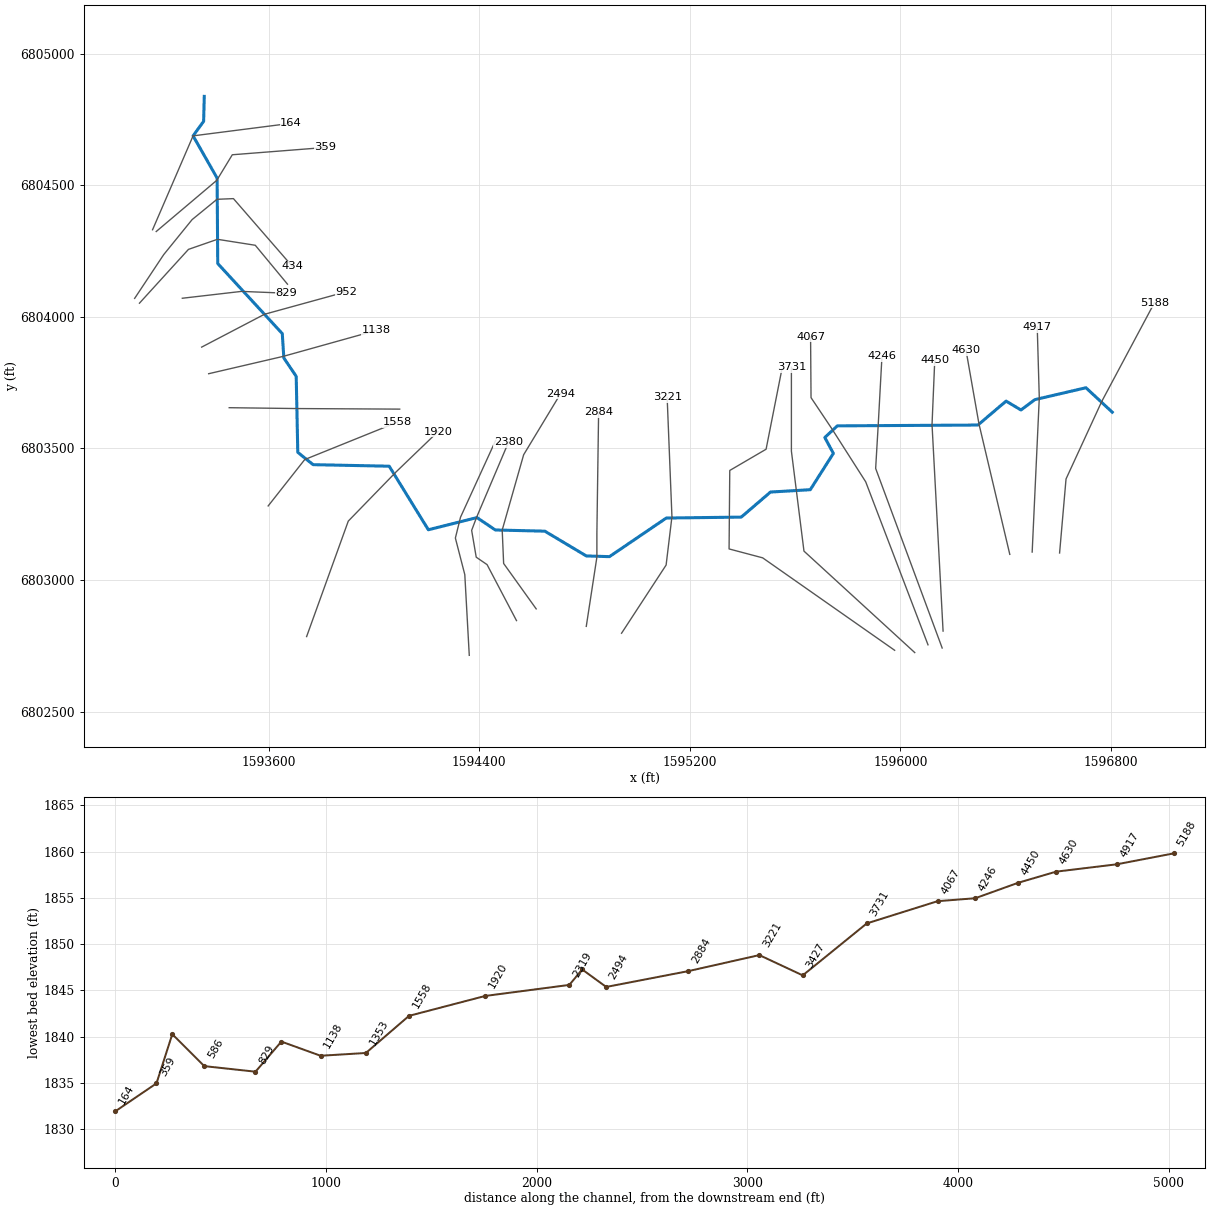
--- Elm 01 80.prj (project) ---

Proj Title=Elm 01 80 Base Level Engineering
Current Plan=p01
Default Exp/Contr=0.3,0.1
English Units
Geom File=g01
Flow File=f01
Plan File=p01
Y Axis Title=Elevation
X Axis Title(PF)=Main Channel Distance
X Axis Title(XS)=Station
BEGIN DESCRIPTION:
Elm 01 80
END DESCRIPTION:
DSS Export Rating Curves= 0
DSS Export Rating Curve Sorted= 0
DSS Export Volume Flow Curves= 0
DXF OffsetX= 0
DXF OffsetY= 0
DXF ScaleX= 1
DXF ScaleY= 10

--- Elm 01 80.p01 (plan) ---

Plan Title=Multiple Run
Short Identifier=Multiple
Geom File=g01
Flow File=f01
Subcritical Flow
K Sum by GR= 0
Std Step Tol= 0.01
Critical Tol= 0.01
Num of Std Step Trials= 20
Max Error Tol= 0.3
Flow Tol Ratio= 0.001
Split Flow NTrial= 30
Split Flow Tol= 0.02
Split Flow Ratio= 0.02
Log Output Level= 0
Friction Slope Method= 1
Unsteady Friction Slope Method= 2
Unsteady Bridges Friction Slope Method= 1
Parabolic Critical Depth
Global Vel Dist=  1 , 1 , 1
Global Log Level= 0
CheckData=True
Encroach Param= -1, 0, 0, 0
BEGIN DESCRIPTION:
Multiple Run
END DESCRIPTION:

--- Elm 01 80.f01 (steady flow) ---

Flow Title=Multiple
Program Version=4.10
Number of Profiles= 7
Profile Names=10-year,25-year,50-year,1pct_min,100-year,1pct_plu,500-year
River Rch & RM=Elm 01 80,Reach-1         ,5188
     126     166     198     146     234     322     332
River Rch & RM=Elm 01 80,Reach-1         ,3731
     245     337     412     312     500     688     747
River Rch & RM=Elm 01 80,Reach-1         ,3427
     307     427     527     402     645     887     979
Boundary for River Rch & Prof#=Elm 01 80,Reach-1         , 1
Up Type= 0
Dn Type= 3
Dn Slope=0.01
Boundary for River Rch & Prof#=Elm 01 80,Reach-1         , 2
Up Type= 0
Dn Type= 3
Dn Slope=0.01
Boundary for River Rch & Prof#=Elm 01 80,Reach-1         , 3
Up Type= 0
Dn Type= 3
Dn Slope=0.01
Boundary for River Rch & Prof#=Elm 01 80,Reach-1         , 4
Up Type= 0
Dn Type= 3
Dn Slope=0.01
Boundary for River Rch & Prof#=Elm 01 80,Reach-1         , 5
Up Type= 0
Dn Type= 3
Dn Slope=0.01
Boundary for River Rch & Prof#=Elm 01 80,Reach-1         , 6
Up Type= 0
Dn Type= 3
Dn Slope=0.01
Boundary for River Rch & Prof#=Elm 01 80,Reach-1         , 7
Up Type= 0
Dn Type= 3
Dn Slope=0.01
DSS Import GetInterval= 0
DSS Import GetPeak= 0
DSS Import FillOption= 0

--- Elm 01 80.g01 (geometry) ---

Geom Title=Existing Conditions

River Reach=Elm 01 80,Reach-1
Reach XY= 30
      1596805.00      6803638.00      1596705.11      6803730.78
      1596510.86      6803685.54      1596458.21      6803646.29
      1596401.67      6803679.99      1596294.57      6803589.06
      1595760.46      6803585.94      1595712.87      6803541.62
      1595745.41      6803481.46      1595657.70      6803343.36
      1595506.47      6803334.44      1595395.41      6803239.21
      1595110.52      6803235.65      1594894.52      6803088.94
      1594806.59      6803091.67      1594649.07      6803185.76
      1594460.94      6803190.26      1594391.03      6803237.45
      1594206.42      6803191.04      1594057.70      6803432.64
      1593768.71      6803438.47      1593710.34      6803485.26
      1593704.32      6803774.08      1593657.36      6803843.98
      1593651.39      6803936.50      1593406.15      6804202.81
      1593403.80      6804527.50      1593312.48      6804687.99
      1593352.54      6804743.37      1593355.00      6804838.00

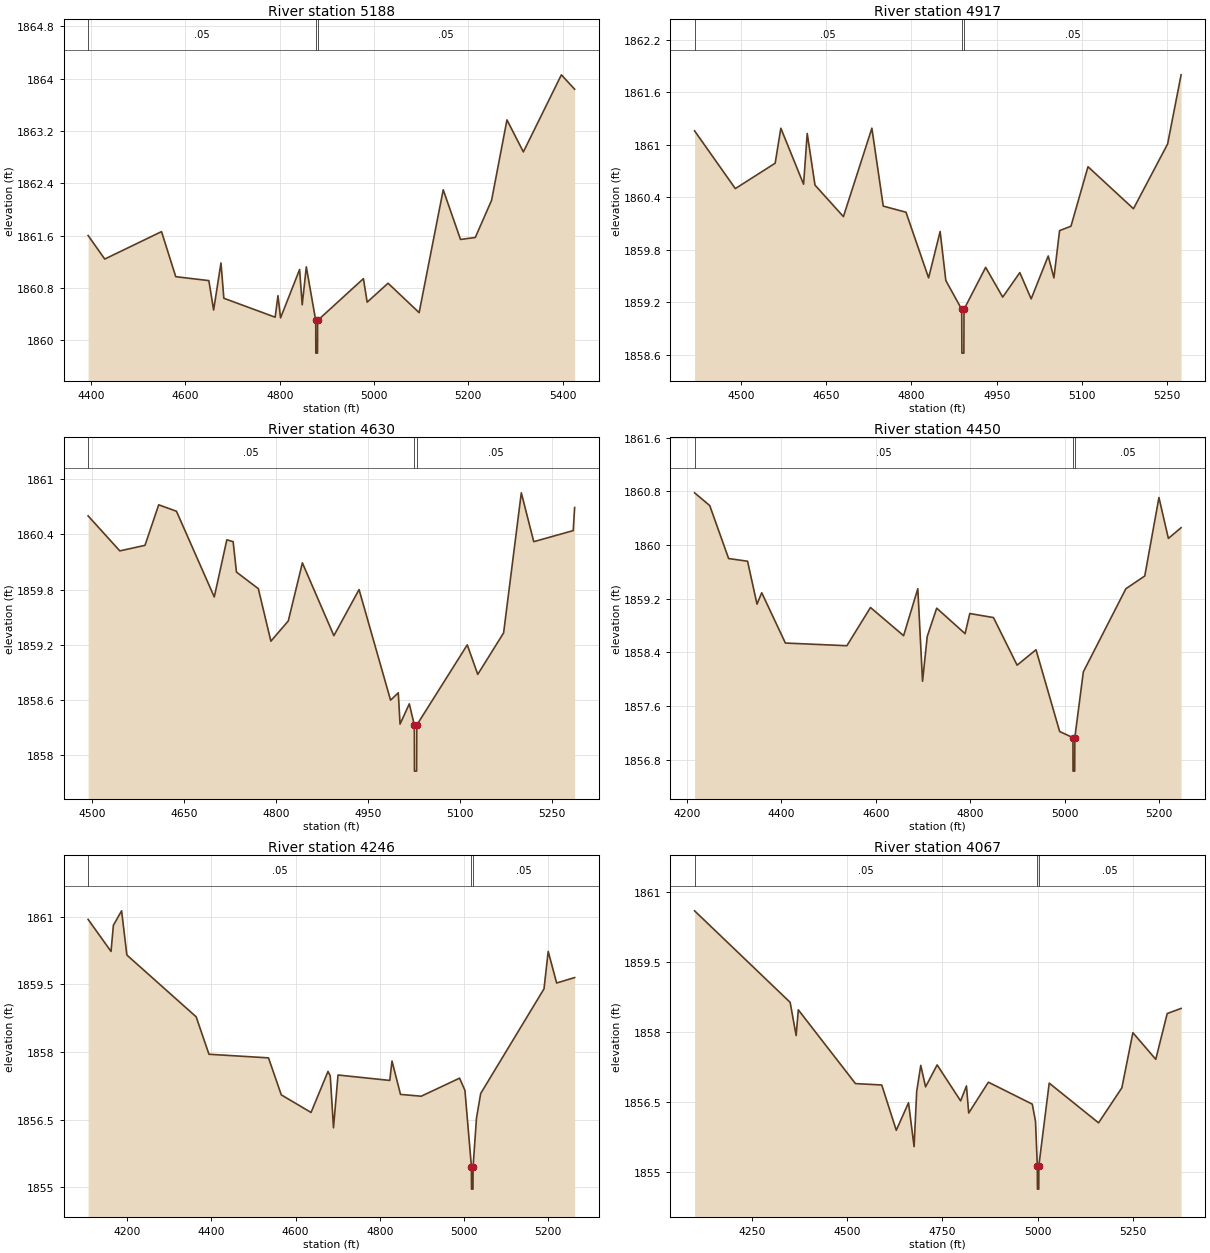
Type RM Length L Ch R = 1,5188,271,271,271
BEGIN DESCRIPTION:
Elm 01 80 4780.364
END DESCRIPTION:
XS GIS Cut Line= 4
      1596604.97      6803102.84      1596629.47      6803384.17
      1596765.02      6803678.46      1596965.33      6804053.86
#Sta/Elev= 30
  4393.6 1861.60  4428.9 1861.24  4549.3 1861.66  4579.5 1860.97  4649.7 1860.91
  4659.8 1860.46  4675.4 1861.18  4681.5 1860.64  4790.3 1860.35  4796.3 1860.68
  4801.8 1860.34  4842.2 1861.08  4847.7 1860.54  4856.4 1861.12  4876.4 1860.30
  4876.6 1859.80  4880.1 1859.80  4880.4 1860.30  4977.5 1860.94  4985.5 1860.58
  5029.8 1860.87  5095.7 1860.42  5146.8 1862.30  5183.5 1861.54  5214.8 1861.57
  5249.4 1862.14  5282.0 1863.37  5316.8 1862.88  5397.4 1864.06  5425.5 1863.84
#Mann=3,-1,0
  4393.6    0.05       0  4876.4    0.05       0  4880.4    0.05       0
Bank Sta=4876.4,4880.4
Exp/Cntr=0.3,0.1

Type RM Length L Ch R = 1,4917,287,287,287
BEGIN DESCRIPTION:
Elm 01 80 4916.99
END DESCRIPTION:
XS GIS Cut Line= 3
      1596500.81      6803106.36      1596527.83      6803692.16
      1596520.02      6803961.72
#Sta/Elev= 30
  4418.3 1861.16  4490.0 1860.50  4560.1 1860.79  4570.1 1861.19  4610.1 1860.55
  4616.5 1861.13  4630.2 1860.54  4680.2 1860.18  4730.3 1861.19  4750.3 1860.30
  4790.3 1860.23  4830.1 1859.48  4850.4 1860.01  4860.4 1859.45  4888.4 1859.12
  4888.7 1858.62  4892.2 1858.62  4892.4 1859.12  4930.5 1859.60  4960.5 1859.26
  4990.6 1859.54  5010.6 1859.24  5040.6 1859.73  5050.6 1859.48  5060.6 1860.02
  5080.6 1860.07  5110.6 1860.75  5190.6 1860.27  5250.7 1861.01  5274.4 1861.80
#Mann=3,-1,0
  4418.3    0.05       0  4888.4    0.05       0  4892.4    0.05       0
Bank Sta=4888.4,4892.4
Exp/Cntr=0.3,0.1

Type RM Length L Ch R = 1,4630,180,180,180
BEGIN DESCRIPTION:
Elm 01 80 4629.7
END DESCRIPTION:
XS GIS Cut Line= 3
      1596415.74      6803097.65      1596298.67      6803593.20
      1596249.32      6803873.70
#Sta/Elev= 30
  4493.4 1860.60  4545.1 1860.22  4586.2 1860.28  4608.6 1860.72  4637.6 1860.65
  4699.3 1859.72  4719.8 1860.34  4730.1 1860.32  4735.5 1859.99  4771.2 1859.81
  4791.7 1859.24  4820.1 1859.46  4843.1 1860.09  4894.5 1859.30  4935.6 1859.80
  4987.0 1858.60  4999.6 1858.68  5002.5 1858.34  5017.6 1858.56  5025.8 1858.33
  5026.0 1857.83  5029.5 1857.83  5029.8 1858.33  5112.2 1859.20  5129.3 1858.88
  5171.5 1859.33  5200.4 1860.85  5220.7 1860.32  5285.1 1860.44  5287.4 1860.69
#Mann=3,-1,0
  4493.4    0.05       0  5025.8    0.05       0  5029.8    0.05       0
Bank Sta=5025.8,5029.8
Exp/Cntr=0.3,0.1

Type RM Length L Ch R = 1,4450,204,204,204
BEGIN DESCRIPTION:
Elm 01 80 4450.14
END DESCRIPTION:
XS GIS Cut Line= 3
      1596162.27      6802805.99      1596120.28      6803590.59
      1596130.62      6803834.84
#Sta/Elev= 30
  4216.0 1860.78  4248.1 1860.59  4288.1 1859.80  4328.2 1859.76  4348.2 1859.12
  4358.2 1859.29  4408.3 1858.54  4538.5 1858.50  4588.5 1859.07  4658.6 1858.65
  4688.7 1859.35  4698.7 1857.97  4708.7 1858.64  4728.7 1859.06  4788.8 1858.68
  4798.8 1858.98  4848.9 1858.92  4899.0 1858.21  4939.0 1858.44  4989.1 1857.22
  5017.2 1857.13  5017.4 1856.63  5020.9 1856.63  5021.2 1857.13  5039.2 1858.11
  5129.3 1859.35  5169.3 1859.54  5199.3 1860.71  5219.3 1860.10  5246.2 1860.26
#Mann=3,-1,0
  4216.0    0.05       0  5017.2    0.05       0  5021.2    0.05       0
Bank Sta=5017.2,5021.2
Exp/Cntr=0.3,0.1

Type RM Length L Ch R = 1,4246,179,179,179
BEGIN DESCRIPTION:
Elm 01 80 4245.8
END DESCRIPTION:
XS GIS Cut Line= 4
      1596158.81      6802741.72      1595906.06      6803424.11
      1595915.86      6803590.59      1595930.09      6803850.64
#Sta/Elev= 30
  4107.5 1860.94  4161.9 1860.23  4167.5 1860.81  4187.0 1861.13  4199.5 1860.15
  4364.0 1858.78  4394.4 1857.95  4535.7 1857.87  4566.1 1857.05  4636.7 1856.66
  4677.0 1857.57  4682.3 1857.47  4690.0 1856.32  4700.7 1857.49  4823.6 1857.37
  4828.9 1857.80  4849.1 1857.06  4898.2 1857.02  4989.3 1857.42  5002.0 1857.15
  5017.4 1855.46  5017.6 1854.96  5021.1 1854.96  5021.4 1855.46  5029.4 1856.53
  5039.4 1857.08  5189.7 1859.40  5199.7 1860.23  5219.7 1859.53  5262.4 1859.65
#Mann=3,-1,0
  4107.5    0.05       0  5017.4    0.05       0  5021.4    0.05       0
Bank Sta=5017.4,5021.4
Exp/Cntr=0.3,0.1

Type RM Length L Ch R = 1,4067,336,336,336
BEGIN DESCRIPTION:
Elm 01 80 4066.92
END DESCRIPTION:
XS GIS Cut Line= 5
      1596104.96      6802753.95      1595868.25      6803373.31
      1595738.77      6803576.27      1595660.54      6803693.16
      1595658.80      6803924.40
#Sta/Elev= 30
  4100.1 1860.60  4350.7 1858.64  4366.4 1857.93  4372.1 1858.48  4522.0 1856.90
  4590.9 1856.87  4629.0 1855.90  4661.1 1856.49  4675.7 1855.55  4682.5 1856.73
  4693.2 1857.29  4705.8 1856.83  4736.1 1857.30  4797.7 1856.53  4813.0 1856.85
  4818.9 1856.27  4870.5 1856.93  4985.6 1856.46  4994.1 1856.09  4998.8 1855.14
  4999.1 1854.64  5002.6 1854.64  5002.8 1855.14  5030.0 1856.91  5159.4 1856.06
  5220.5 1856.81  5249.4 1857.99  5309.4 1857.42  5339.4 1858.40  5375.8 1858.51
#Mann=3,-1,0
  4100.1    0.05       0  4998.8    0.05       0  5002.8    0.05       0
Bank Sta=4998.8,5002.8
Exp/Cntr=0.3,0.1

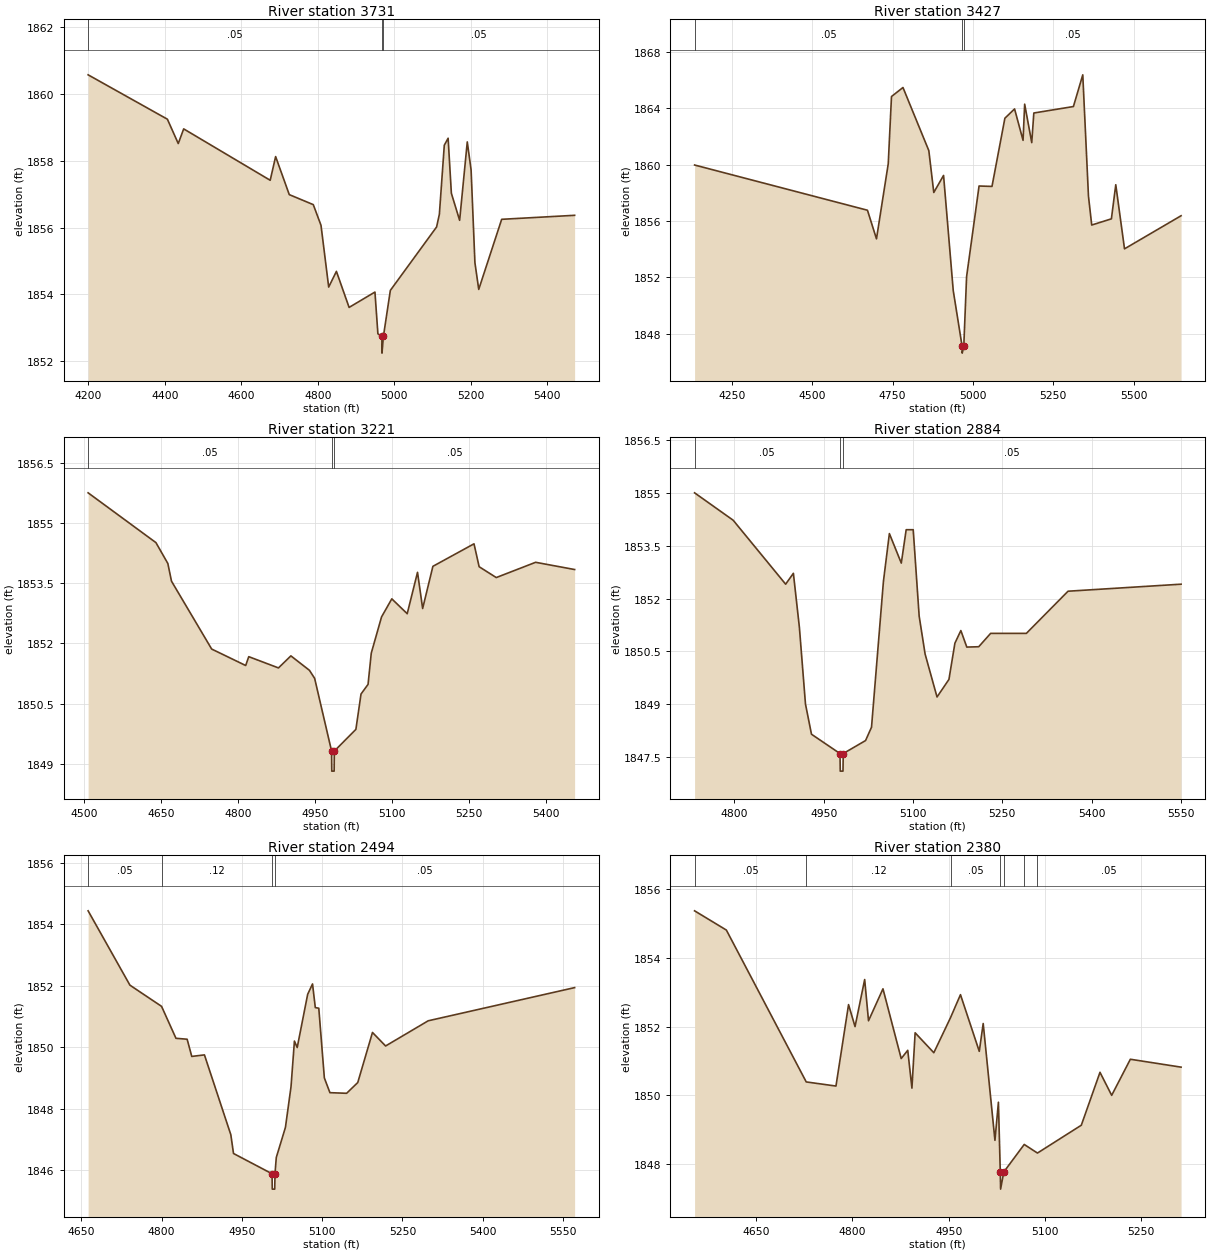
Type RM Length L Ch R = 1,3731,304,304,304
BEGIN DESCRIPTION:
Mapping XS b7c47f65
END DESCRIPTION:
XS GIS Cut Line= 4
      1596054.61      6802724.41      1595633.69      6803109.95
      1595585.95      6803489.72      1595585.95      6803808.76
#Sta/Elev= 30
  4199.3 1860.58  4406.7 1859.25  4435.1 1858.52  4449.3 1858.96  4675.6 1857.42
  4689.8 1858.13  4725.5 1856.99  4788.3 1856.69  4808.5 1856.07  4828.6 1854.22
  4848.8 1854.69  4882.0 1853.61  4949.6 1854.07  4957.3 1852.82  4967.7 1852.74
  4968.0 1852.24  4971.7 1852.74  4989.9 1854.12  5110.8 1856.02  5118.1 1856.40
  5131.0 1858.47  5141.0 1858.68  5149.5 1857.03  5171.1 1856.22  5191.1 1858.57
  5201.1 1857.73  5211.1 1854.95  5221.1 1854.15  5281.1 1856.25  5471.9 1856.37
#Mann=3,-1,0
  4199.3    0.05       0  4967.7    0.03       0  4971.7    0.05       0
Bank Sta=4967.7,4971.7
Exp/Cntr=0.3,0.1

Type RM Length L Ch R = 1,3427,206,206,206
BEGIN DESCRIPTION:
Elm 01 80 3426.99
END DESCRIPTION:
XS GIS Cut Line= 6
      1595978.20      6802733.10      1595476.73      6803084.41
      1595349.12      6803118.26      1595351.73      6803416.44
      1595489.75      6803497.17      1595549.65      6803800.60
#Sta/Elev= 30
  4134.4 1859.98  4672.0 1856.77  4700.0 1854.74  4736.6 1860.07  4746.7 1864.84
  4782.4 1865.48  4862.8 1861.00  4878.2 1858.03  4908.6 1859.24  4938.7 1851.07
  4966.2 1847.13  4966.6 1846.63  4971.5 1847.13  4980.2 1852.05  5019.0 1858.49
  5059.2 1858.46  5099.3 1863.30  5129.4 1863.96  5155.8 1861.73  5160.8 1864.30
  5182.8 1861.57  5189.3 1863.67  5312.4 1864.13  5341.5 1866.38  5359.2 1857.77
  5369.3 1855.72  5430.5 1856.16  5444.1 1858.58  5471.3 1854.03  5647.2 1856.38
#Mann=3,-1,0
  4134.4    0.05       0  4966.2    0.03       0  4971.5    0.05       0
Bank Sta=4966.2,4971.5
Exp/Cntr=0.3,0.1

Type RM Length L Ch R = 1,3221,337,337,337
BEGIN DESCRIPTION:
Elm 01 80 3220.83
END DESCRIPTION:
XS GIS Cut Line= 4
      1594940.58      6802797.88      1595109.87      6803057.02
      1595132.00      6803240.61      1595113.81      6803693.99
#Sta/Elev= 30
  4508.3 1855.75  4640.5 1854.51  4663.7 1853.99  4670.8 1853.55  4749.1 1851.86
  4815.4 1851.45  4821.4 1851.67  4879.3 1851.39  4903.5 1851.69  4939.7 1851.33
  4949.8 1851.13  4982.8 1849.32  4983.2 1848.82  4987.8 1848.82  4988.2 1849.32
  5030.2 1849.86  5040.2 1850.74  5053.9 1850.98  5060.2 1851.76  5080.2 1852.66
  5100.2 1853.11  5130.2 1852.74  5150.3 1853.77  5160.3 1852.87  5180.3 1853.92
  5260.4 1854.48  5270.4 1853.91  5303.8 1853.64  5380.5 1854.02  5456.5 1853.84
#Mann=3,-1,0
  4508.3    0.05       0  4982.8    0.03       0  4988.2    0.05       0
Bank Sta=4982.8,4988.2
Exp/Cntr=0.3,0.1

Type RM Length L Ch R = 1,2884,390,390,390
BEGIN DESCRIPTION:
Elm 01 80 2884.06
END DESCRIPTION:
XS GIS Cut Line= 4
      1594806.49      6802823.99      1594846.84      6803086.97
      1594846.84      6803179.42      1594853.36      6803637.77
#Sta/Elev= 30
  4733.3 1855.01  4798.1 1854.23  4886.2 1852.41  4899.2 1852.72  4909.3 1851.18
  4919.5 1849.00  4929.6 1848.14  4977.5 1847.59  4977.9 1847.09  4982.5 1847.09
  4982.9 1847.59  5020.4 1847.96  5030.4 1848.34  5050.4 1852.49  5060.4 1853.85
  5080.4 1853.01  5088.6 1853.96  5100.4 1853.96  5110.4 1851.50  5120.4 1850.42
  5140.4 1849.20  5160.4 1849.70  5170.4 1850.73  5180.4 1851.09  5190.4 1850.62
  5210.4 1850.63  5230.4 1851.01  5290.4 1851.01  5360.4 1852.21  5550.2 1852.41
#Mann=3,-1,0
  4733.3    0.05       0  4977.5    0.05       0  4982.9    0.05       0
Bank Sta=4977.5,4982.9
Exp/Cntr=0.3,0.1

Type RM Length L Ch R = 1,2494,114,114,114
BEGIN DESCRIPTION:
Elm 01 80 2493.75
END DESCRIPTION:
XS GIS Cut Line= 5
      1594616.21      6802890.44      1594492.50      6803062.99
      1594487.07      6803189.94      1594568.52      6803476.13
      1594709.15      6803708.79
#Sta/Elev= 30
  4662.9 1854.44  4741.0 1852.02  4800.1 1851.33  4827.0 1850.29  4847.9 1850.26
  4856.5 1849.70  4880.2 1849.75  4929.5 1847.15  4934.5 1846.54  5006.5 1845.88
  5006.9 1845.38  5011.5 1845.38  5012.0 1845.88  5014.4 1846.41  5031.5 1847.39
  5041.9 1848.71  5048.3 1850.20  5053.5 1849.99  5073.0 1851.72  5082.1 1852.06
  5087.3 1851.29  5093.8 1851.27  5104.2 1849.00  5114.6 1848.52  5145.8 1848.50
  5166.6 1848.85  5194.1 1850.48  5218.6 1850.04  5298.2 1850.86  5571.7 1851.94
#Mann=4,-1,0
  4662.9    0.05       0  4800.1    0.12       0  5006.5    0.07       0
  5012.0    0.05       0
Bank Sta=5006.5,5012
Exp/Cntr=0.3,0.1

Type RM Length L Ch R = 1,2380,61,61,61
BEGIN DESCRIPTION:
Elm 01 80 2380.23
END DESCRIPTION:
XS GIS Cut Line= 6
      1594541.34      6802845.94      1594429.56      6803058.65
      1594388.33      6803086.86      1594370.97      6803188.86
      1594389.42      6803237.68      1594511.32      6803524.65
#Sta/Elev= 30
  4554.3 1855.37  4603.8 1854.81  4728.2 1850.39  4774.5 1850.27  4794.1 1852.64
  4804.2 1852.00  4819.2 1853.37  4825.2 1852.17  4847.7 1853.10  4876.1 1851.07
  4886.3 1851.31  4892.8 1850.21  4897.8 1851.82  4926.9 1851.24  4952.9 1852.26
  4968.4 1852.93  4997.7 1851.28  5003.8 1852.09  5022.1 1848.69  5027.5 1849.80
  5030.4 1847.77  5030.9 1847.27  5035.9 1847.77  5067.7 1848.57  5088.3 1848.32
  5156.6 1849.13  5185.7 1850.67  5203.9 1850.00  5233.0 1851.05  5312.0 1850.82
#Mann=7,-1,0
  4554.3    0.05       0  4728.2    0.12       0  4952.9    0.05       0
  5030.4    0.03       0  5035.9    0.05       0  5067.7    0.12       0
  5088.3    0.05       0
Bank Sta=5030.4,5035.9
Exp/Cntr=0.3,0.1

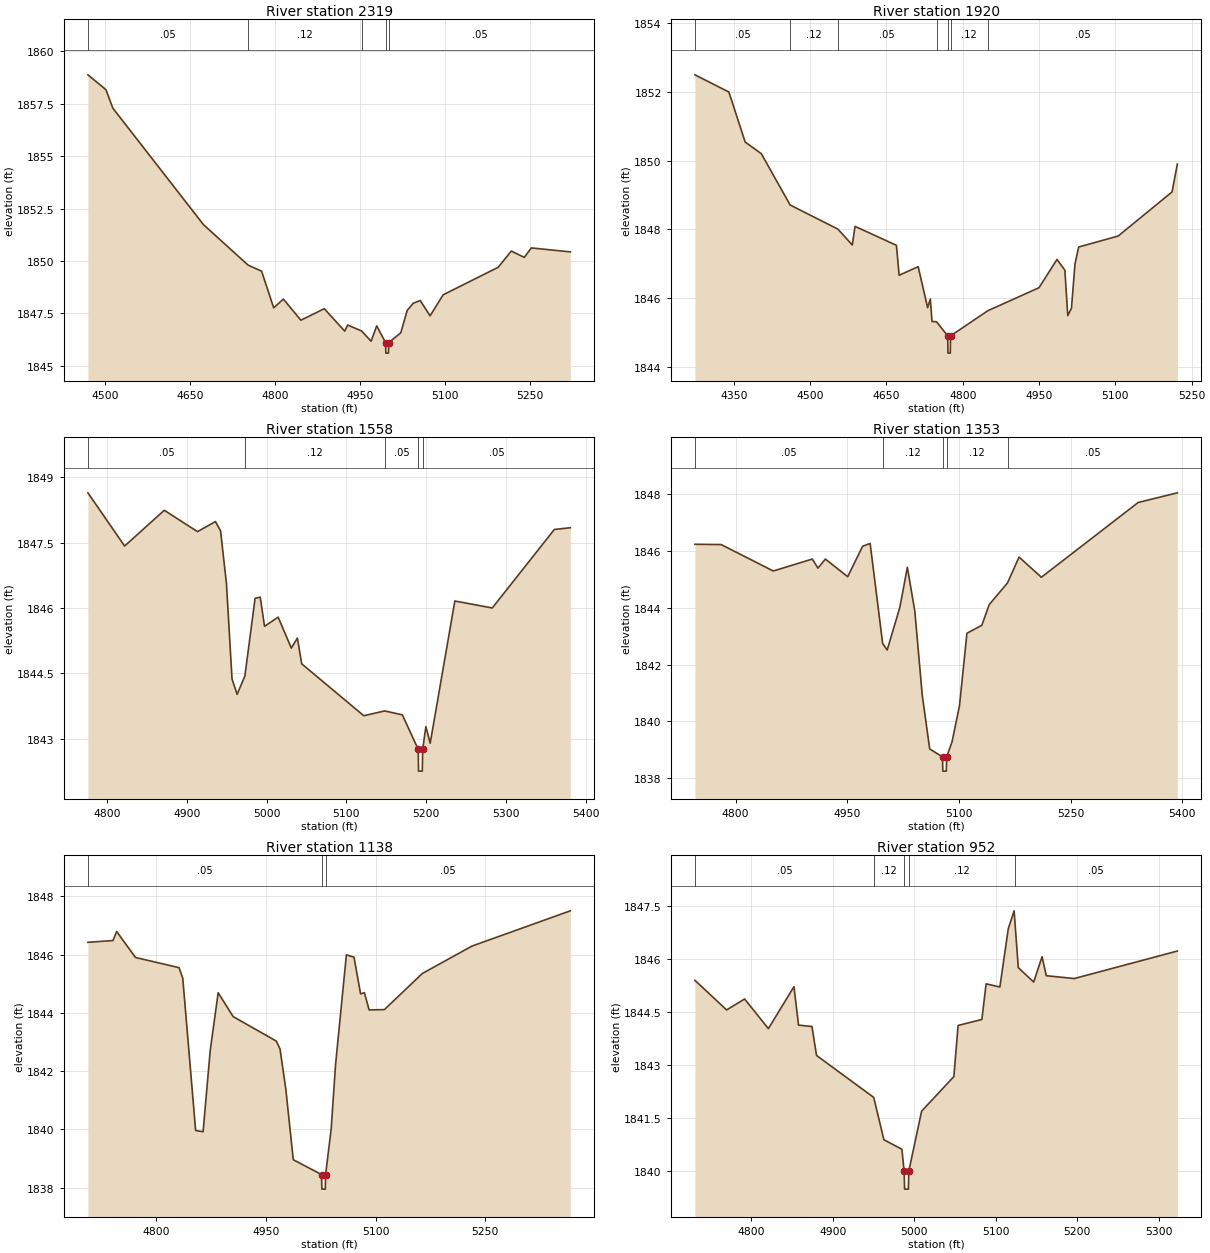
Type RM Length L Ch R = 1,2319,399,399,399
BEGIN DESCRIPTION:
Elm 01 80 2319.21
END DESCRIPTION:
XS GIS Cut Line= 5
      1594361.92      6802713.95      1594344.93      6803020.67
      1594309.12      6803159.56      1594328.65      6803238.77
      1594462.13      6803530.69
#Sta/Elev= 30
  4468.9 1858.88  4500.8 1858.17  4513.0 1857.29  4673.3 1851.73  4752.2 1849.80
  4776.1 1849.51  4797.5 1847.76  4814.6 1848.18  4845.6 1847.17  4886.9 1847.72
  4923.1 1846.65  4928.3 1846.94  4952.8 1846.66  4969.8 1846.17  4979.7 1846.90
  4995.4 1846.10  4995.8 1845.60  5000.4 1845.60  5000.9 1846.10  5022.3 1846.57
  5033.6 1847.64  5044.2 1847.98  5056.6 1848.11  5074.1 1847.38  5097.1 1848.38
  5194.7 1849.70  5217.7 1850.47  5240.7 1850.17  5253.2 1850.62  5322.1 1850.43
#Mann=5,-1,0
  4468.9    0.05       0  4752.2    0.12       0  4952.8    0.05       0
  4995.4    0.03       0  5000.9    0.05       0
Bank Sta=4995.4,5000.9
Exp/Cntr=0.3,0.1

Type RM Length L Ch R = 1,1920,362,362,362
BEGIN DESCRIPTION:
Elm 01 80 1920.07
END DESCRIPTION:
XS GIS Cut Line= 4
      1593743.88      6802785.20      1593902.19      6803224.02
      1594083.90      6803410.99      1594243.21      6803564.27
#Sta/Elev= 30
  4273.5 1852.49  4340.3 1851.99  4372.2 1850.54  4404.0 1850.20  4460.7 1848.71
  4554.6 1848.01  4582.8 1847.55  4588.2 1848.09  4669.6 1847.54  4674.9 1846.67
  4712.3 1846.92  4730.9 1845.73  4736.2 1845.98  4739.5 1845.33  4748.5 1845.32
  4770.4 1844.91  4770.9 1844.41  4775.5 1844.41  4775.9 1844.91  4849.2 1845.64
  4949.9 1846.31  4985.2 1847.13  5000.7 1846.82  5006.4 1845.50  5013.6 1845.71
  5020.6 1847.00  5027.8 1847.49  5105.5 1847.81  5211.4 1849.09  5221.8 1849.90
#Mann=7,-1,0
  4273.5    0.05       0  4460.7    0.12       0  4554.6    0.05       0
  4748.5    0.12       0  4770.4    0.03       0  4775.9    0.12       0
  4849.2    0.05       0
Bank Sta=4770.4,4775.9
Exp/Cntr=0.3,0.1

Type RM Length L Ch R = 1,1558,205,205,205
BEGIN DESCRIPTION:
Elm 01 80 1557.73
END DESCRIPTION:
XS GIS Cut Line= 3
      1593597.79      6803281.65      1593736.68      6803457.87
      1594089.14      6803600.24
#Sta/Elev= 30
  4776.2 1848.64  4822.2 1847.42  4871.9 1848.24  4913.5 1847.75  4936.0 1847.98
  4942.4 1847.77  4949.8 1846.56  4956.8 1844.37  4963.2 1844.02  4972.9 1844.44
  4985.7 1846.22  4992.1 1846.25  4997.5 1845.58  5014.6 1845.79  5031.1 1845.08
  5038.7 1845.31  5044.1 1844.72  5121.9 1843.53  5148.1 1843.64  5170.2 1843.55
  5190.1 1842.76  5190.5 1842.26  5195.2 1842.26  5195.7 1842.76  5199.7 1843.28
  5205.1 1842.90  5236.0 1846.16  5282.9 1846.00  5360.7 1847.80  5380.7 1847.84
#Mann=5,-1,0
  4776.2    0.05       0  4972.9    0.12       0  5148.1    0.05       0
  5190.1    0.07       0  5195.7    0.05       0
Bank Sta=5190.1,5195.7
Exp/Cntr=0.3,0.1

Type RM Length L Ch R = 1,1353,215,215,215
BEGIN DESCRIPTION:
Elm 01 80 1352.62
END DESCRIPTION:
XS GIS Cut Line= 3
      1593449.77      6803654.97      1593705.88      6803651.71
      1594097.64      6803649.54
#Sta/Elev= 30
  4745.3 1846.23  4780.5 1846.22  4850.5 1845.29  4902.9 1845.71  4910.5 1845.39
  4920.5 1845.71  4950.5 1845.09  4970.5 1846.16  4980.6 1846.26  4997.4 1842.74
  5003.5 1842.51  5020.6 1844.02  5030.6 1845.42  5040.6 1843.88  5050.6 1840.92
  5060.6 1839.03  5077.8 1838.75  5078.2 1838.25  5082.9 1838.25  5083.4 1838.75
  5090.6 1839.28  5100.6 1840.55  5110.6 1843.10  5130.6 1843.38  5140.6 1844.11
  5165.1 1844.87  5180.6 1845.78  5210.6 1845.07  5340.6 1847.70  5393.2 1848.04
#Mann=5,-1,0
  4745.3    0.05       0  4997.4    0.12       0  5077.8    0.07       0
  5083.4    0.12       0  5165.1    0.05       0
Bank Sta=5077.8,5083.4
Exp/Cntr=0.3,0.1

Type RM Length L Ch R = 1,1138,186,186,186
BEGIN DESCRIPTION:
Elm 01 80 1138.31
END DESCRIPTION:
XS GIS Cut Line= 3
      1593371.68      6803784.09      1593655.97      6803850.28
      1594009.75      6803949.04
#Sta/Elev= 30
  4706.9 1846.42  4741.1 1846.48  4746.2 1846.79  4771.9 1845.90  4831.4 1845.55
  4836.5 1845.19  4854.1 1839.96  4864.3 1839.92  4874.0 1842.70  4884.9 1844.69
  4905.4 1843.87  4964.3 1843.03  4969.4 1842.76  4977.3 1841.39  4987.5 1838.96
  5026.1 1838.45  5026.6 1837.95  5031.3 1837.95  5031.7 1838.45  5039.3 1840.01
  5045.3 1842.22  5060.1 1845.99  5070.5 1845.91  5079.5 1844.65  5084.7 1844.69
  5091.2 1844.10  5112.0 1844.11  5163.9 1845.35  5231.7 1846.29  5366.1 1847.50
#Mann=3,-1,0
  4706.9    0.05       0  5026.1    0.05       0  5031.7    0.05       0
Bank Sta=5026.1,5031.7
Exp/Cntr=0.3,0.1

Type RM Length L Ch R = 1,952,123,123,123
BEGIN DESCRIPTION:
Elm 01 80 951.97
END DESCRIPTION:
XS GIS Cut Line= 3
      1593345.04      6803885.20      1593583.72      6804009.97
      1593895.12      6804095.68
#Sta/Elev= 30
  4730.7 1845.40  4769.6 1844.56  4791.7 1844.87  4820.9 1844.03  4852.3 1845.22
  4857.9 1844.13  4874.4 1844.09  4880.0 1843.27  4950.2 1842.08  4962.7 1840.88
  4984.8 1840.61  4987.6 1839.98  4988.1 1839.48  4992.8 1839.48  4993.2 1839.98
  5009.0 1841.69  5048.6 1842.67  5053.8 1844.12  5083.0 1844.29  5088.2 1845.30
  5105.1 1845.21  5115.4 1846.86  5122.6 1847.37  5123.9 1846.96  5127.7 1845.76
  5146.6 1845.35  5156.9 1846.07  5162.1 1845.53  5196.5 1845.45  5323.0 1846.23
#Mann=5,-1,0
  4730.7    0.05       0  4950.2    0.12       0  4987.6    0.07       0
  4993.2    0.12       0  5123.9    0.05       0
Bank Sta=4987.6,4993.2
Exp/Cntr=0.3,0.1

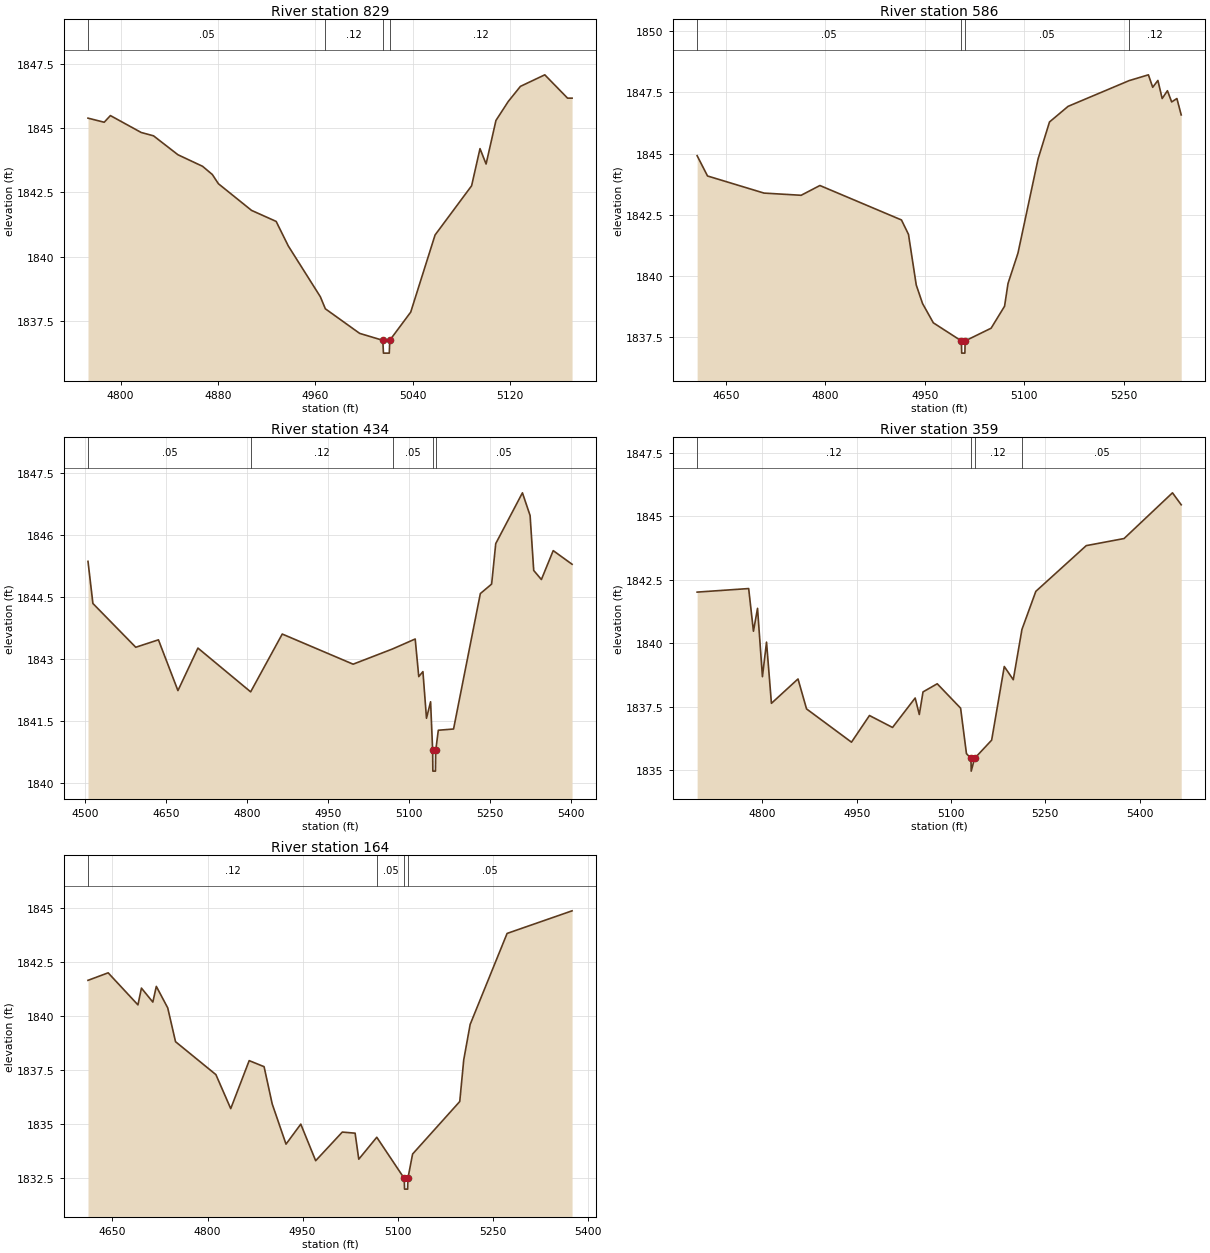
Type RM Length L Ch R = 1,829,243,243,243
BEGIN DESCRIPTION:
Elm 01 80 828.98
END DESCRIPTION:
XS GIS Cut Line= 3
      1593271.55      6804070.91      1593496.38      6804096.95
      1593667.40      6804090.01
#Sta/Elev= 30
  4773.3 1845.40  4786.6 1845.24  4791.7 1845.50  4817.0 1844.84  4827.1 1844.71
  4847.2 1843.97  4867.4 1843.52  4875.4 1843.20  4880.4 1842.84  4907.6 1841.80
  4927.8 1841.37  4937.8 1840.41  4964.1 1838.43  4968.2 1837.96  4996.4 1837.00
  5015.4 1836.73  5015.9 1836.23  5020.7 1836.23  5021.1 1836.73  5038.3 1837.83
  5058.3 1840.84  5088.3 1842.76  5095.2 1844.21  5100.2 1843.61  5108.3 1845.31
  5118.4 1846.05  5128.4 1846.64  5148.4 1847.09  5167.1 1846.18  5170.8 1846.18
#Mann=4,-1,0
  4773.3    0.05       0  4968.2    0.12       0  5015.4    0.07       0
  5021.1    0.12       0
Bank Sta=5015.4,5021.1
Exp/Cntr=0.3,0.1

Type RM Length L Ch R = 1,586,152,152,152
BEGIN DESCRIPTION:
Elm 01 80 585.93
END DESCRIPTION:
XS GIS Cut Line= 5
      1593108.68      6804052.15      1593294.90      6804256.60
      1593405.00      6804294.87      1593548.81      6804272.23
      1593671.19      6804124.41
#Sta/Elev= 30
  4606.4 1844.91  4622.1 1844.08  4707.3 1843.38  4763.4 1843.29  4791.7 1843.69
  4914.8 1842.28  4925.4 1841.69  4937.1 1839.62  4946.6 1838.86  4962.9 1838.07
  5005.2 1837.33  5005.7 1836.83  5010.5 1836.83  5010.9 1837.33  5050.1 1837.85
  5070.4 1838.75  5075.6 1839.68  5090.6 1840.92  5121.0 1844.78  5138.2 1846.29
  5166.3 1846.93  5258.1 1847.98  5287.5 1848.22  5294.0 1847.71  5301.8 1847.99
  5308.3 1847.25  5316.2 1847.57  5322.6 1847.11  5330.5 1847.25  5337.0 1846.58
#Mann=4,-1,0
  4606.4    0.05       0  5005.2    0.05       0  5010.9    0.05       0
  5258.1    0.12       0
Bank Sta=5005.2,5010.9
Exp/Cntr=0.3,0.1

Type RM Length L Ch R = 1,434,75,75,75
BEGIN DESCRIPTION:
Elm 01 80 433.55
END DESCRIPTION:
XS GIS Cut Line= 6
      1593090.47      6804070.40      1593200.65      6804236.42
      1593308.70      6804369.64      1593403.32      6804446.90
      1593465.82      6804449.50      1593689.19      6804192.37
#Sta/Elev= 30
  4506.0 1845.36  4515.1 1844.34  4594.4 1843.28  4636.4 1843.46  4672.5 1842.23
  4709.5 1843.26  4807.1 1842.20  4865.6 1843.60  4996.8 1842.87  5070.0 1843.24
  5111.7 1843.48  5118.3 1842.57  5126.0 1842.69  5132.6 1841.56  5140.2 1841.96
  5144.0 1840.78  5144.4 1840.28  5149.2 1840.28  5149.7 1840.78  5154.5 1841.27
  5182.7 1841.30  5232.3 1844.58  5253.2 1844.81  5260.8 1845.79  5310.2 1847.02
  5324.4 1846.47  5331.1 1845.14  5345.3 1844.92  5367.2 1845.62  5402.1 1845.29
#Mann=5,-1,0
  4506.0    0.05       0  4807.1    0.12       0  5070.0    0.05       0
  5144.0    0.07       0  5149.7    0.05       0
Bank Sta=5144,5149.7
Exp/Cntr=0.3,0.1

Type RM Length L Ch R = 1,359,195,195,195
BEGIN DESCRIPTION:
Elm 01 80 359.25
END DESCRIPTION:
XS GIS Cut Line= 4
      1593172.41      6804324.49      1593402.45      6804518.95
      1593461.48      6804616.17      1593815.64      6804643.94
#Sta/Elev= 30
  4696.1 1842.02  4778.1 1842.16  4785.7 1840.48  4792.2 1841.38  4800.0 1838.69
  4806.5 1840.05  4814.3 1837.64  4856.6 1838.60  4870.2 1837.42  4941.7 1836.11
  4970.3 1837.16  5007.0 1836.69  5043.0 1837.85  5049.6 1837.20  5055.5 1838.09
  5078.1 1838.41  5115.3 1837.45  5124.6 1835.66  5131.8 1835.47  5132.2 1834.97
  5137.5 1835.47  5164.7 1836.19  5184.8 1839.09  5199.1 1838.57  5212.9 1840.55
  5235.0 1842.05  5315.2 1843.85  5375.4 1844.13  5452.4 1845.93  5466.3 1845.46
#Mann=4,-1,0
  4696.1    0.12       0  5131.8    0.07       0  5137.5    0.12       0
  5212.9    0.05       0
Bank Sta=5131.8,5137.5
Exp/Cntr=0.3,0.1

Type RM Length L Ch R = 1,164,0,0,0
BEGIN DESCRIPTION:
Elm 01 80 2381.913
END DESCRIPTION:
XS GIS Cut Line= 3
      1593158.54      6804331.19      1593312.48      6804687.99
      1593684.54      6804735.67
#Sta/Elev= 30
  4611.4 1841.66  4643.2 1842.01  4690.2 1840.52  4695.7 1841.30  4713.7 1840.65
  4719.2 1841.38  4737.2 1840.38  4749.5 1838.81  4813.2 1837.28  4836.6 1835.70
  4865.7 1837.93  4889.2 1837.65  4902.0 1835.92  4923.8 1834.05  4947.1 1834.98
  4970.6 1833.28  5012.6 1834.61  5032.8 1834.56  5038.6 1833.35  5067.0 1834.37
  5110.3 1832.46  5110.8 1831.96  5115.7 1831.96  5116.1 1832.46  5123.5 1833.59
  5197.9 1836.03  5204.2 1837.97  5214.3 1839.61  5272.6 1843.84  5375.1 1844.89
#Mann=4,-1,0
  4611.4    0.12       0  5067.0    0.05       0  5110.3    0.07       0
  5116.1    0.05       0
Bank Sta=5110.3,5116.1
Exp/Cntr=0.3,0.1

Chan Stop Cuts=-1