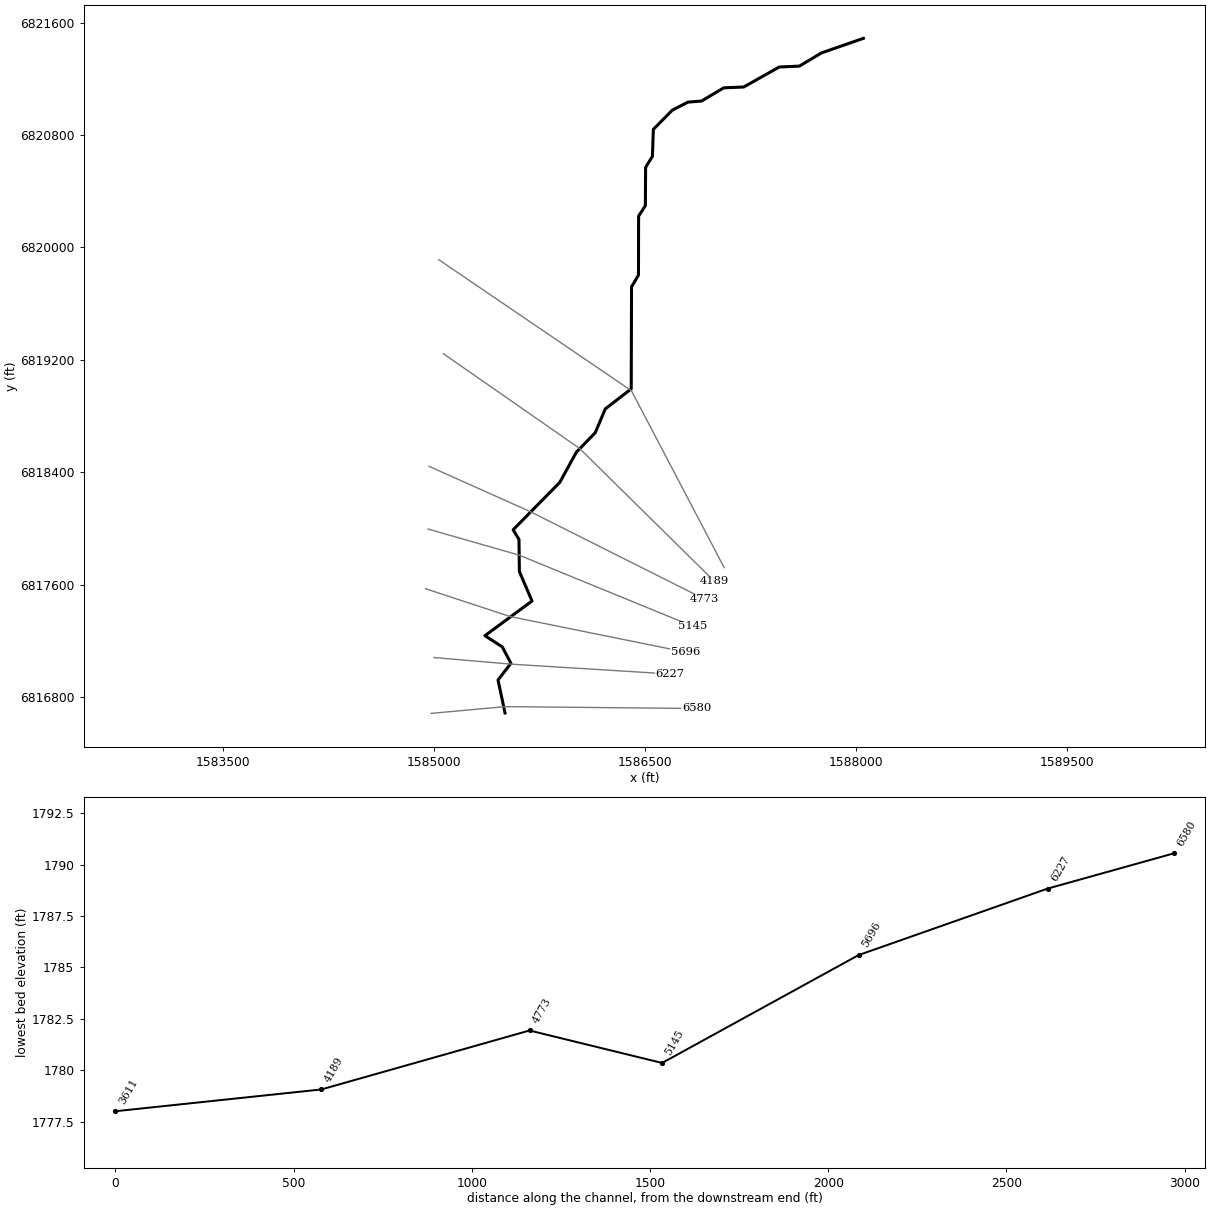
--- Elm 01 82.prj (project) ---

Proj Title=Elm 01 82 Base Level Engineering
Current Plan=p01
Default Exp/Contr=0.3,0.1
English Units
Geom File=g01
Flow File=f01
Plan File=p01
BEGIN DESCRIPTION:
Elm 01 82
END DESCRIPTION:

--- Elm 01 82.p01 (plan) ---

Plan Title=Multiple Run
Short Identifier=Multiple
Geom File=g01
Flow File=f01
Subcritical Flow
K Sum by GR= 0
Std Step Tol= 0.01
Critical Tol= 0.01
Num of Std Step Trials= 20
Max Error Tol= 0.3
Flow Tol Ratio= 0.001
Split Flow NTrial= 30
Split Flow Tol= 0.02
Split Flow Ratio= 0.02
Log Output Level= 0
Friction Slope Method= 1
Unsteady Friction Slope Method= 2
Unsteady Bridges Friction Slope Method= 1
Parabolic Critical Depth
Global Vel Dist=  1 , 1 , 1
Global Log Level= 0
CheckData=True
Encroach Param= -1, 0, 0, 0
BEGIN DESCRIPTION:
Multiple Run
END DESCRIPTION:

--- Elm 01 82.f01 (steady flow) ---

Flow Title=Multiple
Number of Profiles=7
Profile Names=10-year,25-year,50-year,1pct_min,100-year,1pct_plu,500-year
River Rch & RM= Elm 01 82,Reach-1,6580
     177     239     289     217     348     479     511
Boundary for River Rch & Prof#=Elm 01 82,Reach-1,1
Up Type=0
Dn Type=3
Dn Slope=0.001
Boundary for River Rch & Prof#=Elm 01 82,Reach-1,2
Up Type=0
Dn Type=3
Dn Slope=0.001
Boundary for River Rch & Prof#=Elm 01 82,Reach-1,3
Up Type=0
Dn Type=3
Dn Slope=0.001
Boundary for River Rch & Prof#=Elm 01 82,Reach-1,4
Up Type=0
Dn Type=3
Dn Slope=0.001
Boundary for River Rch & Prof#=Elm 01 82,Reach-1,5
Up Type=0
Dn Type=3
Dn Slope=0.001
Boundary for River Rch & Prof#=Elm 01 82,Reach-1,6
Up Type=0
Dn Type=3
Dn Slope=0.001
Boundary for River Rch & Prof#=Elm 01 82,Reach-1,7
Up Type=0
Dn Type=3
Dn Slope=0.001

--- Elm 01 82.g01 (geometry) ---

Geom Title=Existing Conditions

River Reach=Elm 01 82,Reach-1
Reach XY= 30
      1585505.00      6816688.00      1585455.25      6816922.78
      1585547.16      6817041.24      1585485.38      6817158.47
      1585361.98      6817237.80      1585697.21      6817484.57
      1585607.26      6817693.94      1585604.34      6817922.84
      1585562.79      6817991.42      1585894.22      6818328.32
      1586013.16      6818544.05      1586146.86      6818681.94
      1586218.47      6818851.57      1586402.95      6818993.84
      1586405.21      6819719.73      1586454.48      6819803.22
      1586455.52      6820222.78      1586503.62      6820297.66
      1586505.21      6820569.73      1586553.78      6820648.51
      1586560.46      6820840.45      1586695.32      6820977.24
      1586806.58      6821034.17      1586903.42      6821041.83
      1587060.93      6821135.75      1587203.44      6821141.76
      1587456.56      6821284.24      1587599.07      6821290.25
      1587756.58      6821384.17      1588055.00      6821488.00

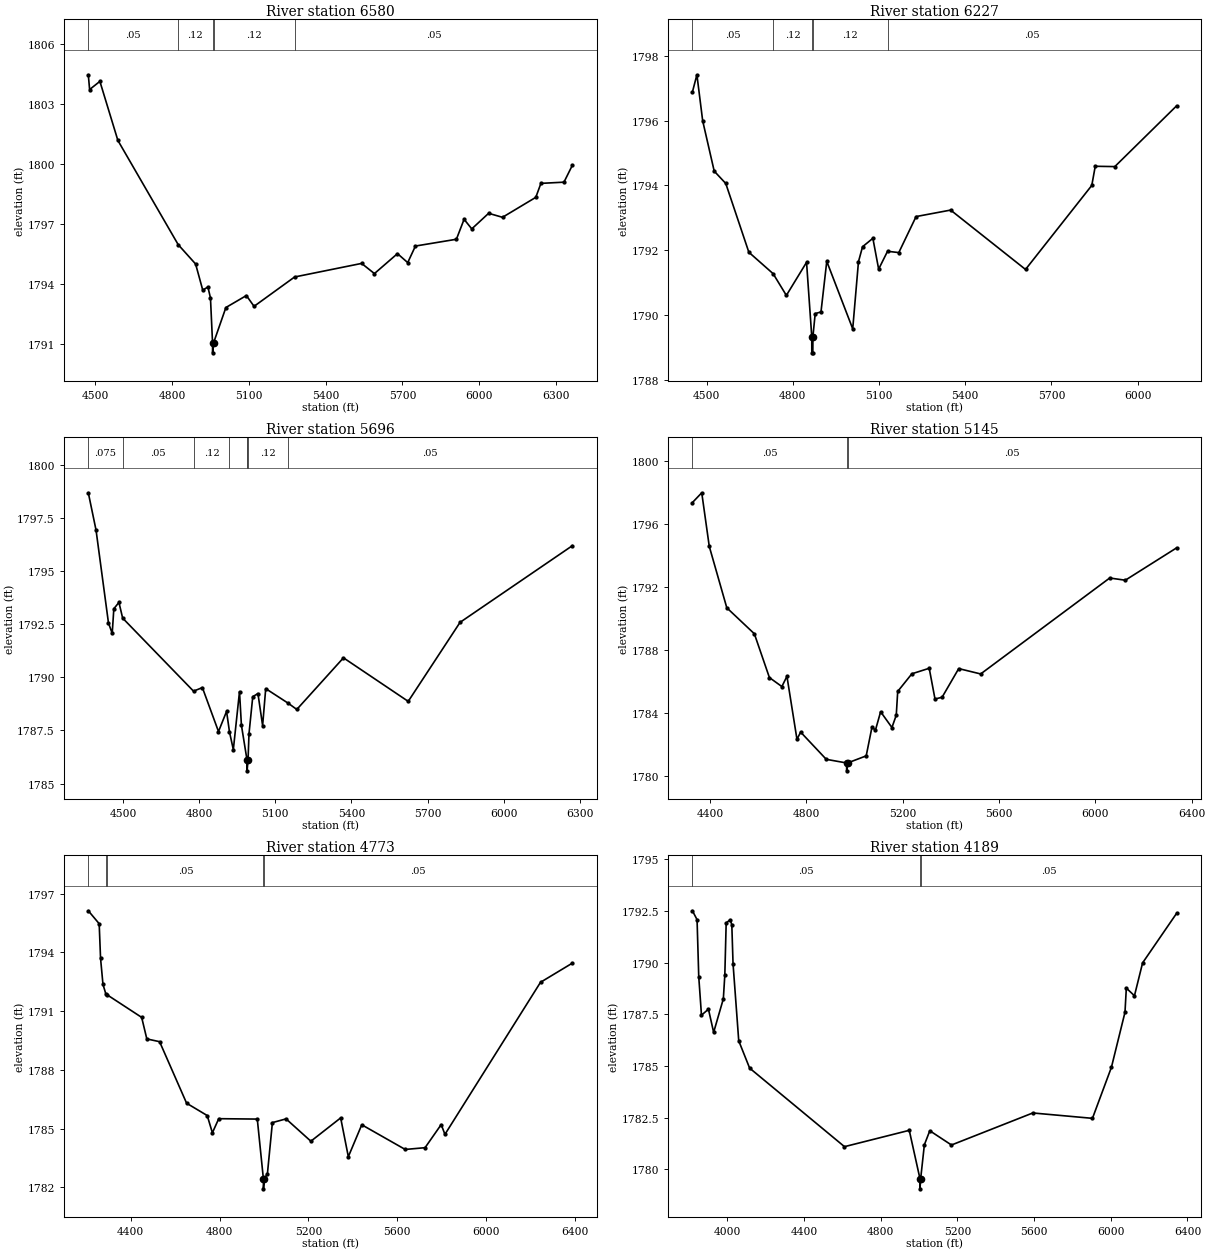
Type RM Length L Ch R = 1,6580,353,353,353
BEGIN DESCRIPTION:
Elm 01 82 5099.734
END DESCRIPTION:
XS GIS Cut Line= 3
      1584979.97      6816685.12      1585504.49      6816733.05
      1586867.92      6816719.84
#Sta/Elev= 30
  4473.3 1804.48  4478.4 1803.74  4518.5 1804.15  4588.8 1801.19  4824.3 1795.97
  4892.3 1795.00  4920.2 1793.69  4940.3 1793.85  4950.3 1793.30  4958.4 1791.05
  4958.6 1790.55  4962.4 1791.05  5010.5 1792.82  5090.5 1793.42  5120.5 1792.88
  5278.8 1794.35  5540.5 1795.03  5590.5 1794.52  5680.5 1795.52  5720.5 1795.07
  5750.6 1795.90  5910.6 1796.24  5940.6 1797.24  5970.6 1796.76  6036.4 1797.54
  6090.6 1797.34  6220.6 1798.34  6240.6 1799.04  6330.6 1799.10  6363.5 1799.95
#Mann=5,-1,0
  4473.3    0.05       0  4824.3    0.12       0  4958.4    0.07       0
  4962.4    0.12       0  5278.8    0.05       0
Bank Sta=4958.4,4962.4
Exp/Cntr=0.3,0.1

Type RM Length L Ch R = 1,6227,531,531,531
BEGIN DESCRIPTION:
Elm 01 82 6226.53
END DESCRIPTION:
XS GIS Cut Line= 3
      1584999.44      6817082.49      1585546.30      6817035.61
      1586679.15      6816965.30
#Sta/Elev= 30
  4451.0 1796.88  4466.6 1797.41  4486.7 1795.99  4526.8 1794.44  4567.0 1794.06
  4647.3 1791.94  4731.7 1791.28  4777.8 1790.61  4848.0 1791.63  4866.1 1789.34
  4866.3 1788.84  4869.8 1788.84  4870.1 1789.34  4878.1 1790.05  4898.2 1790.10
  4918.3 1791.66  5008.6 1789.58  5028.6 1791.65  5042.8 1792.11  5078.7 1792.37
  5098.8 1791.42  5129.7 1791.97  5168.9 1791.93  5229.0 1793.04  5349.2 1793.24
  5609.7 1791.41  5840.2 1794.00  5852.2 1794.59  5920.3 1794.58  6134.9 1796.45
#Mann=5,-1,0
  4451.0    0.05       0  4731.7    0.12       0  4866.1    0.07       0
  4870.1    0.12       0  5129.7    0.05       0
Bank Sta=4866.1,4870.1
Exp/Cntr=0.3,0.1

Type RM Length L Ch R = 1,5696,551,551,551
BEGIN DESCRIPTION:
Elm 01 82 5696.44
END DESCRIPTION:
XS GIS Cut Line= 3
      1584939.54      6817572.07      1585541.10      6817374.15
      1586788.50      6817121.55
#Sta/Elev= 30
  4363.8 1798.69  4394.3 1796.93  4443.2 1792.56  4457.9 1792.07  4464.3 1793.23
  4484.4 1793.53  4499.0 1792.79  4778.1 1789.35  4812.9 1789.52  4876.4 1787.45
  4908.2 1788.40  4919.7 1787.43  4934.8 1786.60  4959.1 1789.33  4966.6 1787.75
  4988.3 1786.14  4988.7 1786.10  4988.9 1785.60  4992.7 1786.10  4996.5 1787.35
  5011.3 1789.09  5031.7 1789.24  5050.1 1787.73  5062.3 1789.47  5151.2 1788.78
  5184.7 1788.49  5368.4 1790.92  5623.4 1788.87  5827.5 1792.59  6269.8 1796.20
#Mann=8,-1,0
  4363.8   0.075       0  4499.0    0.05       0  4778.1    0.12       0
  4919.7    0.05       0  4988.3    0.12       0  4988.7    0.07       0
  4992.7    0.12       0  5151.2    0.05       0
Bank Sta=4988.7,4992.7
Exp/Cntr=0.3,0.1

Type RM Length L Ch R = 1,5145,372,372,372
BEGIN DESCRIPTION:
Elm 01 82 5144.6
END DESCRIPTION:
XS GIS Cut Line= 3
      1584957.78      6817996.54      1585603.60      6817811.65
      1586841.58      6817304.50
#Sta/Elev= 30
  4327.3 1797.38  4366.0 1798.00  4397.2 1794.60  4470.0 1790.70  4584.4 1789.05
  4646.9 1786.27  4698.6 1785.70  4719.7 1786.35  4761.3 1782.35  4776.5 1782.81
  4883.0 1781.08  4967.3 1780.85  4967.6 1780.35  4971.3 1780.85  5048.7 1781.30
  5072.7 1783.13  5087.0 1782.93  5108.6 1784.10  5155.5 1783.10  5173.5 1783.88
  5179.5 1785.39  5238.3 1786.51  5310.3 1786.86  5334.3 1784.91  5363.7 1785.02
  5432.8 1786.84  5523.9 1786.50  6059.6 1792.59  6124.4 1792.45  6336.9 1794.50
#Mann=3,-1,0
  4327.3    0.05       0  4967.3    0.03       0  4971.3    0.05       0
Bank Sta=4967.3,4971.3
Exp/Cntr=0.3,0.1

Type RM Length L Ch R = 1,4773,584,584,584
BEGIN DESCRIPTION:
Elm 01 82 4772.93
END DESCRIPTION:
XS GIS Cut Line= 3
      1584964.74      6818442.71      1585680.85      6818122.42
      1586925.68      6817497.40
#Sta/Elev= 30
  4209.9 1796.12  4258.8 1795.46  4265.0 1793.69  4275.9 1792.36  4288.7 1791.88
  4296.1 1791.82  4449.9 1790.68  4473.1 1789.58  4530.5 1789.44  4652.0 1786.30
  4744.8 1785.67  4768.0 1784.79  4796.6 1785.51  4970.0 1785.49  4997.5 1782.43
  4997.7 1781.93  5001.5 1782.43  5015.6 1782.71  5037.9 1785.31  5099.3 1785.50
  5211.0 1784.36  5345.0 1785.55  5379.5 1783.57  5439.9 1785.20  5635.3 1783.94
  5724.6 1784.03  5797.2 1785.21  5814.0 1784.71  6243.9 1792.47  6387.3 1793.45
#Mann=5,-1,0
  4209.9    0.05       0  4288.7   0.075       0  4296.1    0.05       0
  4997.5    0.03       0  5001.5    0.05       0
Bank Sta=4997.5,5001.5
Exp/Cntr=0.3,0.1

Type RM Length L Ch R = 1,4189,578,578,578
BEGIN DESCRIPTION:
Elm 01 82 4188.74
END DESCRIPTION:
XS GIS Cut Line= 3
      1585066.25      6819244.17      1586035.02      6818570.55
      1586993.32      6817626.14
#Sta/Elev= 30
  3817.3 1792.51  3841.5 1792.08  3850.3 1789.32  3864.5 1787.46  3900.9 1787.75
  3928.0 1786.63  3978.6 1788.25  3986.3 1789.40  3993.4 1791.92  4014.4 1792.08
  4022.8 1791.83  4029.2 1789.95  4058.9 1786.22  4115.7 1784.90  4610.6 1781.10
  4948.5 1781.89  5004.1 1779.56  5004.4 1779.06  5008.1 1779.56  5027.3 1781.19
  5055.6 1781.87  5168.7 1781.18  5593.0 1782.73  5904.2 1782.47  6003.2 1784.94
  6073.9 1787.60  6080.9 1788.77  6123.3 1788.40  6165.8 1789.99  6342.7 1792.38
#Mann=3,-1,0
  3817.3    0.05       0  5004.1    0.03       0  5008.1    0.05       0
Bank Sta=5004.1,5008.1
Exp/Cntr=0.3,0.1

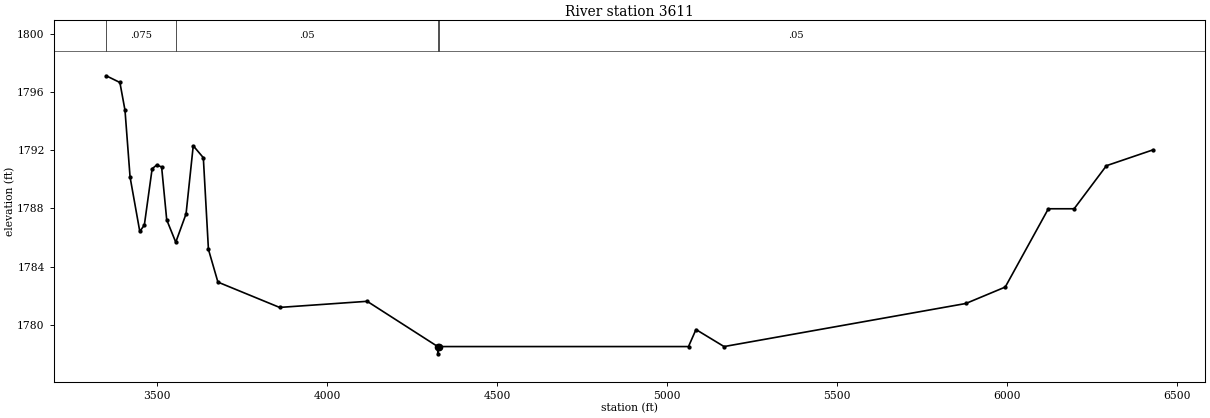
Type RM Length L Ch R = 1,3611,0,0,0
BEGIN DESCRIPTION:
Elm 01 82 3610.98
END DESCRIPTION:
XS GIS Cut Line= 3
      1585033.31      6819913.42      1586404.81      6818980.27
      1587064.14      6817722.34
#Sta/Elev= 30
  3350.0 1797.11  3390.3 1796.65  3405.3 1794.74  3420.2 1790.15  3448.8 1786.41
  3462.2 1786.85  3485.1 1790.72  3498.1 1790.97  3513.0 1790.85  3528.0 1787.21
  3554.6 1785.67  3584.9 1787.62  3606.0 1792.30  3635.7 1791.48  3650.7 1785.18
  3678.6 1782.93  3860.0 1781.19  4117.6 1781.61  4325.1 1778.50  4325.3 1778.00
  4329.1 1778.50  5062.7 1778.50  5084.7 1779.67  5167.3 1778.50  5878.4 1781.46
  5994.3 1782.59  6121.1 1787.97  6196.9 1787.97  6291.9 1790.93  6429.1 1792.02
#Mann=4,-1,0
  3350.0   0.075       0  3554.6    0.05       0  4325.1    0.03       0
  4329.1    0.05       0
Bank Sta=4325.1,4329.1
Exp/Cntr=0.3,0.1

Chan Stop Cuts=-1