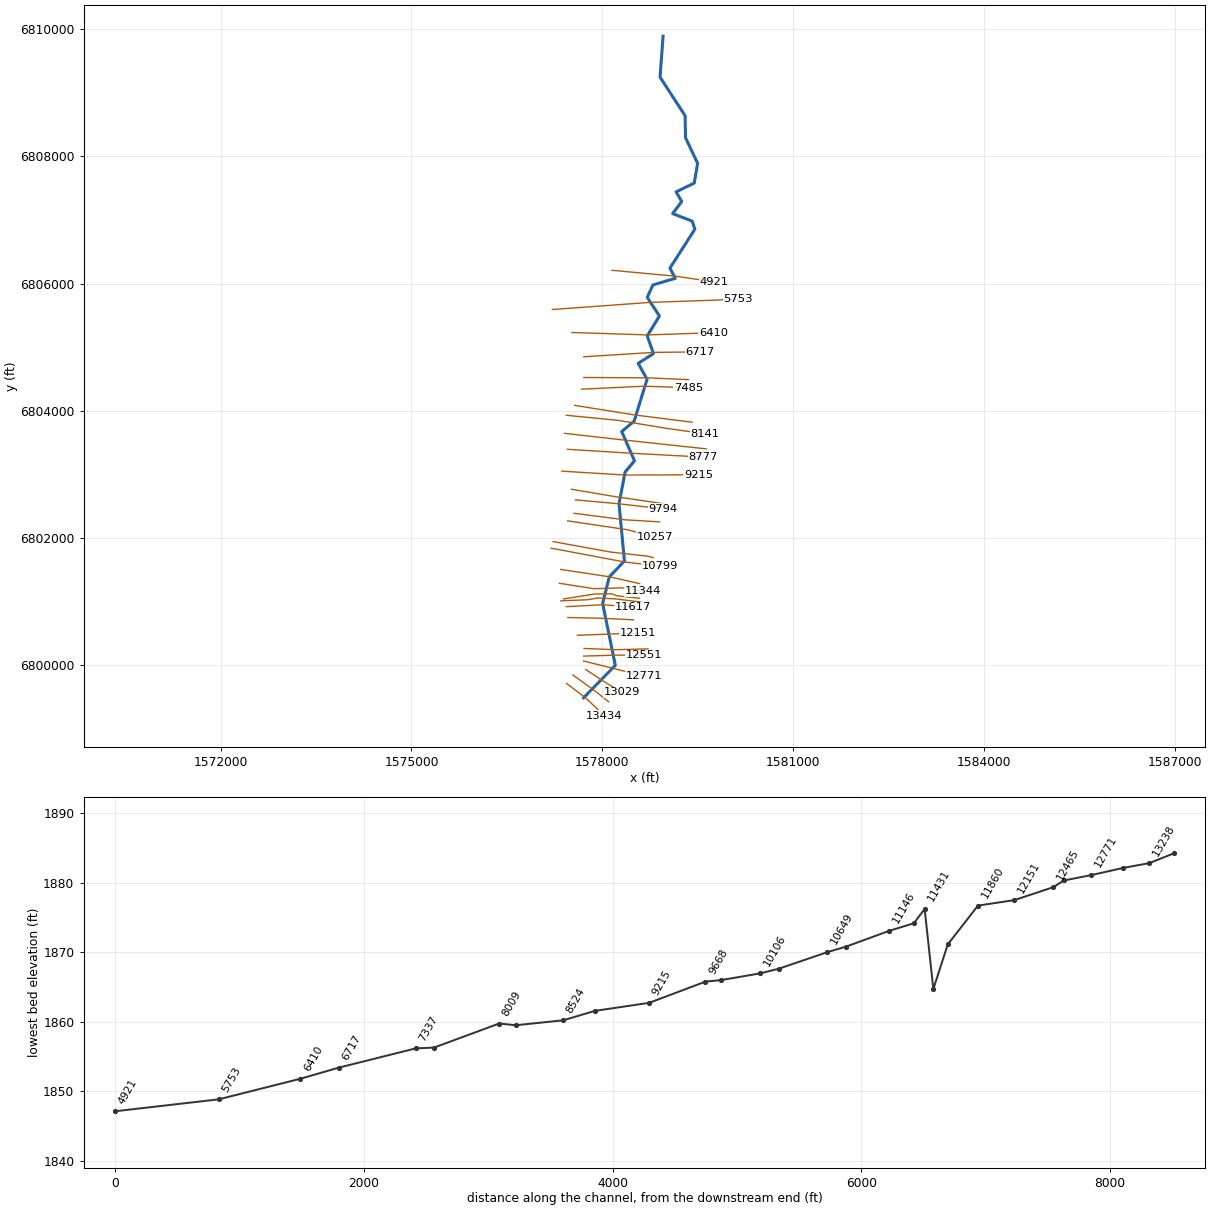
--- Elm 01 83.prj (project) ---

Proj Title=Elm 01 83 Base Level Engineering
Current Plan=p01
Default Exp/Contr=0.3,0.1
English Units
Geom File=g01
Flow File=f01
Plan File=p01
BEGIN DESCRIPTION:
Elm 01 83
END DESCRIPTION:

--- Elm 01 83.p01 (plan) ---

Plan Title=Multiple Run
Short Identifier=Multiple
Geom File=g01
Flow File=f01
Subcritical Flow
K Sum by GR= 0
Std Step Tol= 0.01
Critical Tol= 0.01
Num of Std Step Trials= 20
Max Error Tol= 0.3
Flow Tol Ratio= 0.001
Split Flow NTrial= 30
Split Flow Tol= 0.02
Split Flow Ratio= 0.02
Log Output Level= 0
Friction Slope Method= 1
Unsteady Friction Slope Method= 2
Unsteady Bridges Friction Slope Method= 1
Parabolic Critical Depth
Global Vel Dist=  1 , 1 , 1
Global Log Level= 0
CheckData=True
Encroach Param= -1, 0, 0, 0
BEGIN DESCRIPTION:
Multiple Run
END DESCRIPTION:

--- Elm 01 83.f01 (steady flow) ---

Flow Title=Multiple
Number of Profiles=7
Profile Names=10-year,25-year,50-year,1pct_min,100-year,1pct_plu,500-year
River Rch & RM= Elm 01 83,Reach-1,13434
     192     261     316     238     381     524     561
River Rch & RM= Elm 01 83,Reach-1,5753
     276     382     469     357     572     787     862
Boundary for River Rch & Prof#=Elm 01 83,Reach-1,1
Up Type=0
Dn Type=3
Dn Slope=0.001
Boundary for River Rch & Prof#=Elm 01 83,Reach-1,2
Up Type=0
Dn Type=3
Dn Slope=0.001
Boundary for River Rch & Prof#=Elm 01 83,Reach-1,3
Up Type=0
Dn Type=3
Dn Slope=0.001
Boundary for River Rch & Prof#=Elm 01 83,Reach-1,4
Up Type=0
Dn Type=3
Dn Slope=0.001
Boundary for River Rch & Prof#=Elm 01 83,Reach-1,5
Up Type=0
Dn Type=3
Dn Slope=0.001
Boundary for River Rch & Prof#=Elm 01 83,Reach-1,6
Up Type=0
Dn Type=3
Dn Slope=0.001
Boundary for River Rch & Prof#=Elm 01 83,Reach-1,7
Up Type=0
Dn Type=3
Dn Slope=0.001

--- Elm 01 83.g01 (geometry) ---

Geom Title=Existing Conditions

River Reach=Elm 01 83,Reach-1
Reach XY= 30
      1577705.00      6799488.00      1578203.95      6799998.43
      1578005.09      6800972.61      1578110.82      6801390.31
      1578347.47      6801637.99      1578262.35      6802538.09
      1578358.16      6803036.35      1578505.58      6803213.00
      1578304.94      6803672.67      1578499.58      6803835.33
      1578703.18      6804494.12      1578563.82      6804745.00
      1578803.92      6804898.52      1578705.59      6805177.38
      1578897.69      6805488.11      1578706.72      6805781.52
      1578794.59      6805977.03      1579147.66      6806081.67
      1579062.61      6806241.33      1579454.63      6806853.28
      1579411.53      6806980.32      1579105.53      6807098.68
      1579247.71      6807288.06      1579159.96      6807440.61
      1579444.53      6807578.20      1579497.69      6807887.91
      1579307.24      6808293.93      1579301.45      6808636.53
      1578907.27      6809243.94      1578955.00      6809888.00

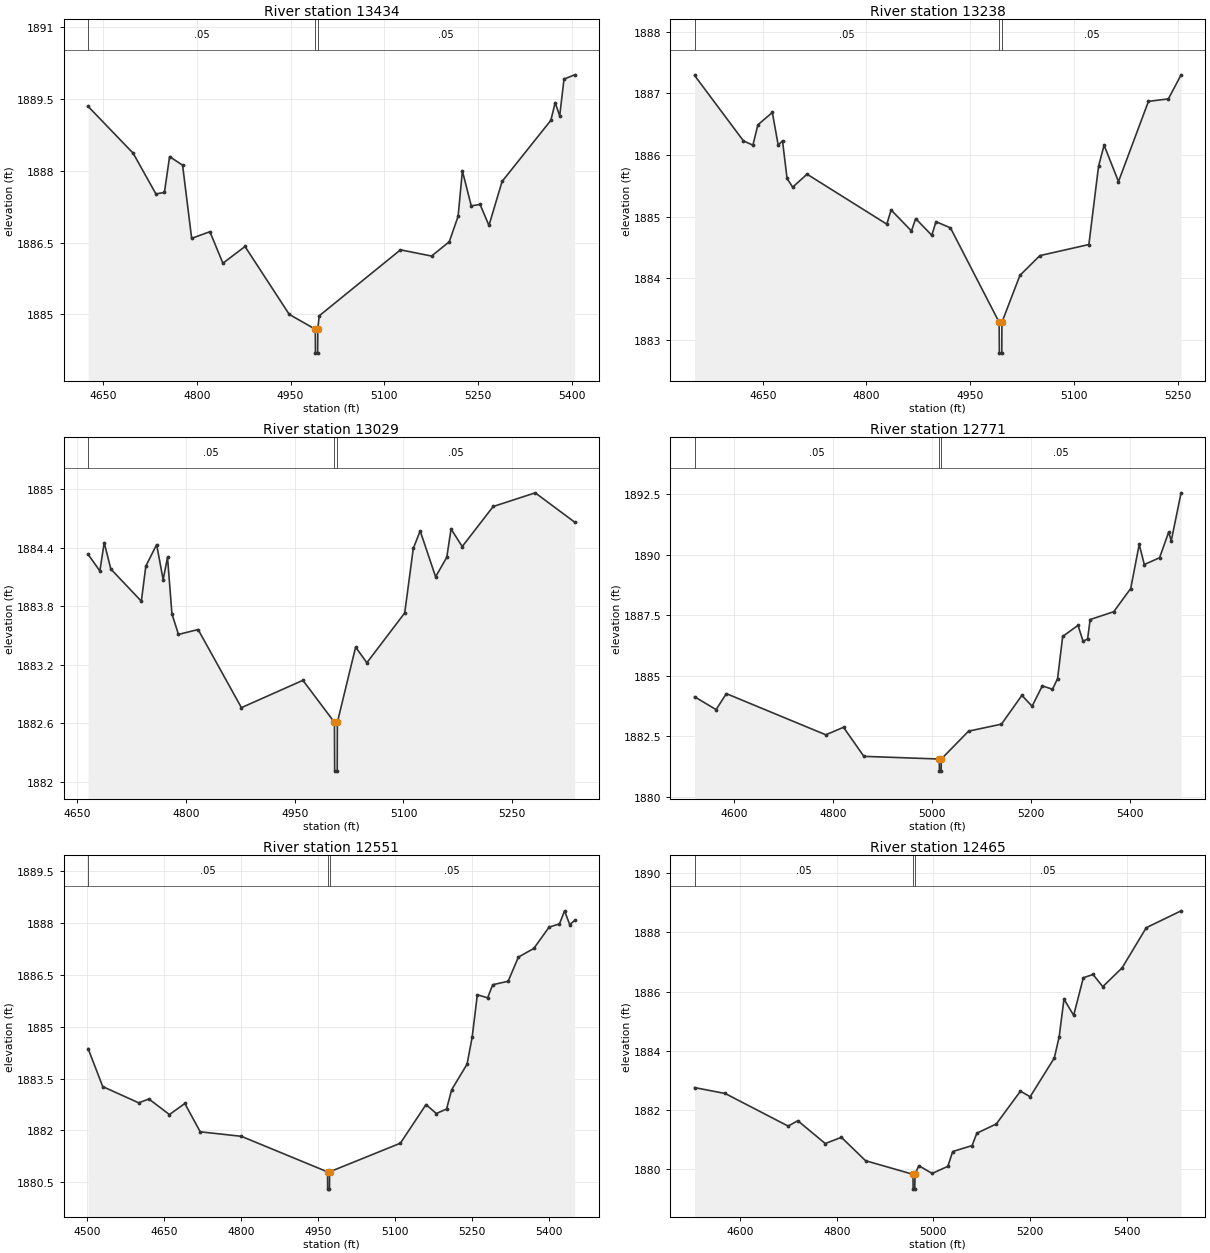
Type RM Length L Ch R = 1,13434,196,196,196
BEGIN DESCRIPTION:
Elm 01 83 12831.758
END DESCRIPTION:
XS GIS Cut Line= 3
      1577438.39      6799713.38      1577736.81      6799488.10
      1578029.73      6799208.85
#Sta/Elev= 30
  4626.1 1889.35  4698.2 1888.37  4734.6 1887.52  4748.2 1887.55  4756.5 1888.30
  4777.3 1888.12  4791.8 1886.59  4821.0 1886.73  4841.8 1886.07  4877.2 1886.42
  4948.0 1885.00  4989.7 1884.69  4989.9 1884.19  4993.4 1884.19  4993.7 1884.69
  4995.9 1884.97  5126.0 1886.35  5175.8 1886.22  5204.1 1886.52  5218.2 1887.05
  5225.1 1888.00  5239.3 1887.27  5253.4 1887.30  5267.6 1886.86  5288.6 1887.78
  5366.7 1889.06  5373.6 1889.43  5380.8 1889.15  5387.7 1889.92  5404.7 1890.01
#Mann=3,-1,0
  4626.1    0.05       0  4989.7    0.05       0  4993.7    0.05       0
Bank Sta=4989.7,4993.7
Exp/Cntr=0.3,0.1

Type RM Length L Ch R = 1,13238,209,209,209
BEGIN DESCRIPTION:
Elm 01 83 13238.48
END DESCRIPTION:
XS GIS Cut Line= 3
      1577536.72      6799847.27      1577899.97      6799584.28
      1578099.22      6799425.40
#Sta/Elev= 30
  4551.5 1887.29  4622.1 1886.23  4635.8 1886.16  4643.0 1886.49  4663.9 1886.69
  4672.4 1886.16  4678.6 1886.23  4685.2 1885.62  4693.3 1885.48  4714.1 1885.69
  4829.4 1884.88  4835.6 1885.11  4865.0 1884.77  4871.1 1884.97  4894.4 1884.70
  4900.5 1884.92  4921.4 1884.82  4991.8 1883.29  4992.1 1882.79  4995.6 1882.79
  4995.8 1883.29  5021.8 1884.05  5050.6 1884.37  5121.5 1884.55  5135.5 1885.82
  5143.5 1886.16  5164.3 1885.57  5207.6 1886.87  5236.4 1886.91  5254.8 1887.30
#Mann=3,-1,0
  4551.5    0.05       0  4991.8    0.05       0  4995.8    0.05       0
Bank Sta=4991.8,4995.8
Exp/Cntr=0.3,0.1

Type RM Length L Ch R = 1,13029,258,258,258
BEGIN DESCRIPTION:
Elm 01 83 13029.36
END DESCRIPTION:
XS GIS Cut Line= 3
      1577738.50      6799933.24      1578017.15      6799749.64
      1578304.91      6799573.86
#Sta/Elev= 30
  4665.1 1884.33  4681.3 1884.16  4687.3 1884.45  4696.4 1884.18  4738.5 1883.85
  4744.7 1884.21  4759.6 1884.43  4768.6 1884.07  4774.6 1884.30  4780.7 1883.72
  4789.7 1883.51  4816.8 1883.56  4876.5 1882.76  4961.3 1883.04  5004.8 1882.61
  5005.1 1882.11  5008.6 1882.11  5008.8 1882.61  5034.0 1883.38  5049.5 1883.22
  5101.7 1883.73  5113.5 1884.39  5123.0 1884.57  5144.3 1884.10  5159.7 1884.30
  5165.6 1884.59  5181.0 1884.41  5223.7 1884.82  5281.7 1884.96  5336.0 1884.66
#Mann=3,-1,0
  4665.1    0.05       0  5004.8    0.05       0  5008.8    0.05       0
Bank Sta=5004.8,5008.8
Exp/Cntr=0.3,0.1

Type RM Length L Ch R = 1,12771,220,220,220
BEGIN DESCRIPTION:
Elm 01 83 12770.53
END DESCRIPTION:
XS GIS Cut Line= 3
      1577702.74      6800067.12      1578168.85      6799951.25
      1578657.13      6799827.55
#Sta/Elev= 30
  4519.7 1884.14  4563.2 1883.61  4583.9 1884.27  4785.1 1882.57  4820.9 1882.88
  4862.1 1881.68  5014.7 1881.57  5014.9 1881.07  5018.4 1881.07  5018.7 1881.57
  5073.8 1882.72  5140.4 1883.01  5181.7 1884.20  5202.3 1883.75  5223.0 1884.59
  5243.6 1884.45  5253.9 1884.89  5264.2 1886.63  5295.2 1887.09  5305.5 1886.43
  5314.6 1886.53  5319.8 1887.33  5367.4 1887.65  5401.8 1888.61  5419.0 1890.43
  5429.3 1889.60  5460.2 1889.88  5478.6 1890.94  5483.8 1890.58  5503.7 1892.56
#Mann=3,-1,0
  4519.7    0.05       0  5014.7    0.03       0  5018.7    0.05       0
Bank Sta=5014.7,5018.7
Exp/Cntr=0.3,0.1

Type RM Length L Ch R = 1,12551,86,86,86
BEGIN DESCRIPTION:
Elm 01 83 12551.04
END DESCRIPTION:
XS GIS Cut Line= 3
      1577706.56      6800143.95      1578207.91      6800158.28
      1578654.55      6800159.58
#Sta/Elev= 30
  4501.6 1884.37  4530.1 1883.27  4600.1 1882.80  4620.1 1882.91  4660.1 1882.46
  4690.1 1882.78  4720.1 1881.96  4800.2 1881.83  4968.2 1880.80  4968.5 1880.30
  4972.0 1880.30  4972.2 1880.80  5110.2 1881.63  5160.2 1882.75  5180.2 1882.49
  5200.2 1882.62  5210.2 1883.18  5240.2 1883.92  5250.2 1884.71  5260.2 1885.93
  5280.2 1885.84  5290.2 1886.22  5320.2 1886.32  5340.2 1887.02  5370.2 1887.27
  5400.2 1887.89  5420.2 1887.98  5430.2 1888.36  5440.2 1887.96  5449.8 1888.08
#Mann=3,-1,0
  4501.6    0.05       0  4968.2    0.03       0  4972.2    0.05       0
Bank Sta=4968.2,4972.2
Exp/Cntr=0.3,0.1

Type RM Length L Ch R = 1,12465,314,314,314
BEGIN DESCRIPTION:
Elm 01 83 12411.029
END DESCRIPTION:
XS GIS Cut Line= 3
      1577711.77      6800263.75      1578205.19      6800244.23
      1578717.02      6800257.24
#Sta/Elev= 30
  4506.2 1882.76  4569.5 1882.56  4699.6 1881.46  4719.6 1881.64  4776.4 1880.87
  4809.7 1881.08  4859.7 1880.29  4957.8 1879.83  4958.0 1879.33  4961.5 1879.33
  4961.8 1879.83  4969.8 1880.12  4997.4 1879.86  5029.8 1880.10  5039.8 1880.60
  5079.8 1880.80  5089.8 1881.22  5129.9 1881.53  5179.9 1882.64  5199.9 1882.45
  5249.9 1883.76  5259.9 1884.47  5269.9 1885.75  5289.9 1885.20  5309.9 1886.47
  5329.9 1886.58  5350.1 1886.17  5389.9 1886.80  5440.0 1888.16  5512.0 1888.73
#Mann=3,-1,0
  4506.2    0.05       0  4957.8    0.05       0  4961.8    0.05       0
Bank Sta=4957.8,4961.8
Exp/Cntr=0.3,0.1

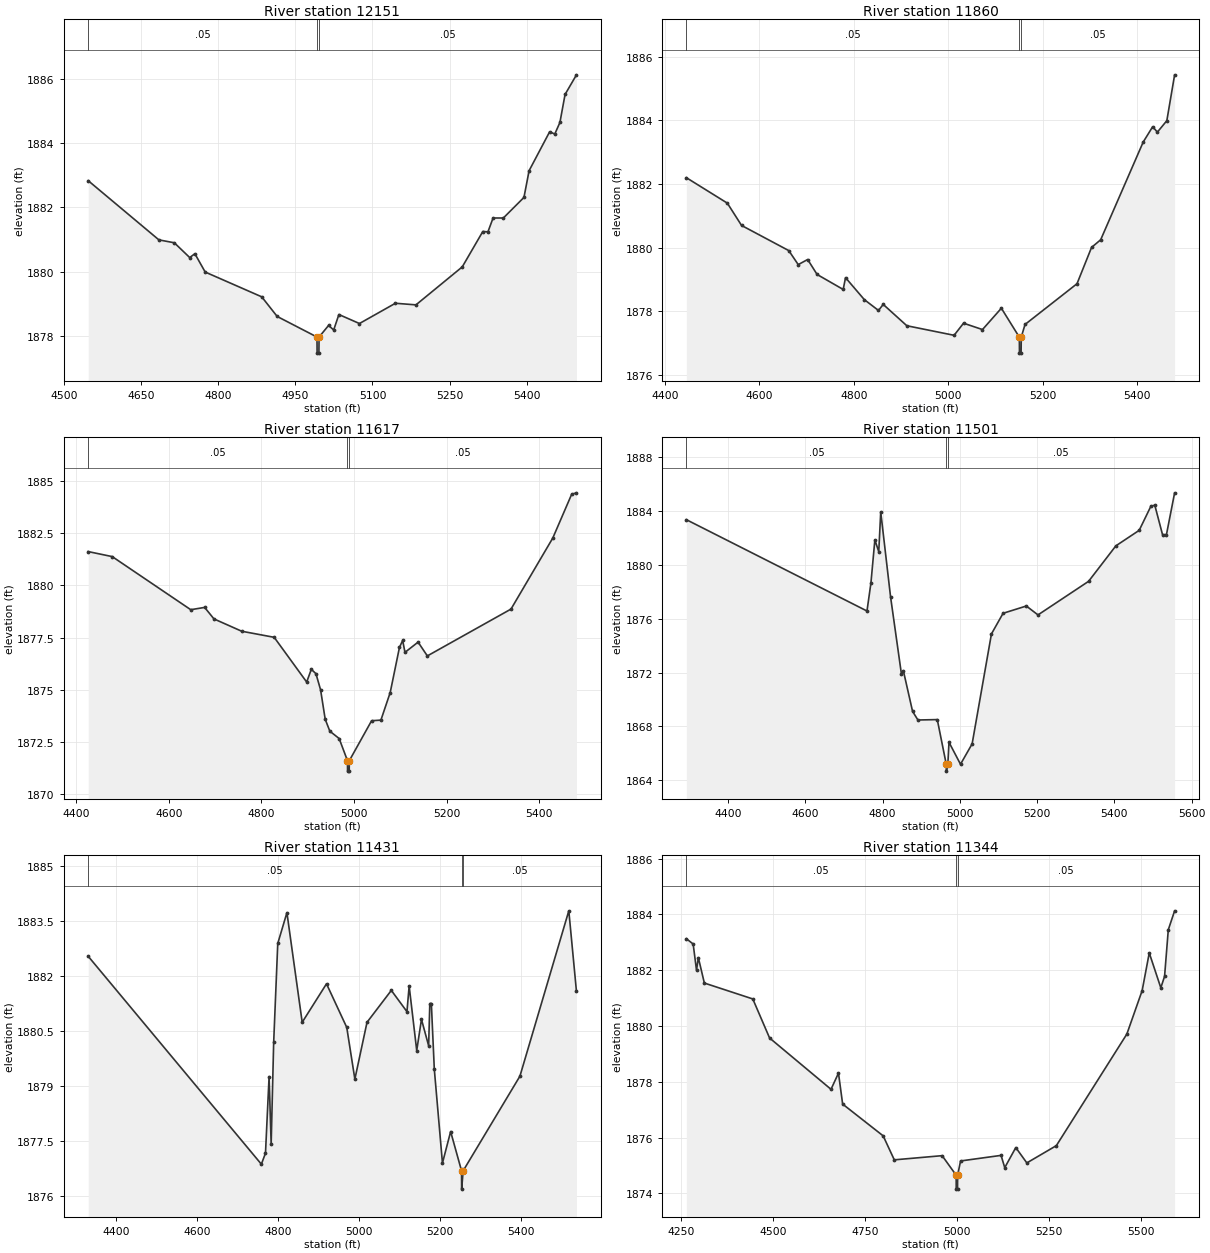
Type RM Length L Ch R = 1,12151,291,291,291
BEGIN DESCRIPTION:
Elm 01 83 12150.8
END DESCRIPTION:
XS GIS Cut Line= 3
      1577607.51      6800470.78      1578058.86      6800488.14
      1578557.17      6800505.50
#Sta/Elev= 30
  4546.8 1882.83  4684.4 1880.99  4714.4 1880.90  4744.4 1880.44  4754.4 1880.56
  4774.5 1879.99  4884.5 1879.22  4914.6 1878.61  4992.1 1877.97  4992.3 1877.47
  4995.8 1877.47  4996.1 1877.97  5014.6 1878.33  5024.6 1878.19  5034.7 1878.67
  5074.7 1878.39  5144.7 1879.02  5184.7 1878.97  5274.8 1880.15  5314.8 1881.25
  5324.8 1881.24  5334.8 1881.67  5354.8 1881.67  5394.9 1882.31  5404.9 1883.14
  5444.9 1884.35  5454.9 1884.28  5464.9 1884.64  5474.9 1885.51  5497.1 1886.12
#Mann=3,-1,0
  4546.8    0.05       0  4992.1    0.05       0  4996.1    0.05       0
Bank Sta=4992.1,4996.1
Exp/Cntr=0.3,0.1

Type RM Length L Ch R = 1,11860,243,243,243
BEGIN DESCRIPTION:
Elm 01 83 11859.53
END DESCRIPTION:
XS GIS Cut Line= 3
      1577458.17      6800750.29      1578011.99      6800738.14
      1578491.43      6800713.91
#Sta/Elev= 30
  4445.4 1882.20  4532.2 1881.40  4562.3 1880.70  4662.3 1879.91  4682.3 1879.47
  4702.3 1879.63  4722.3 1879.16  4777.5 1878.69  4782.5 1879.06  4822.3 1878.37
  4852.3 1878.03  4862.3 1878.22  4912.3 1877.55  5012.4 1877.25  5032.4 1877.63
  5072.5 1877.43  5112.5 1878.10  5150.6 1877.19  5150.8 1876.69  5154.3 1876.69
  5154.6 1877.19  5162.6 1877.59  5272.7 1878.87  5303.5 1880.01  5322.8 1880.25
  5412.9 1883.32  5432.9 1883.80  5442.9 1883.63  5462.9 1883.99  5479.4 1885.43
#Mann=3,-1,0
  4445.4    0.05       0  5150.6    0.05       0  5154.6    0.05       0
Bank Sta=5150.6,5154.6
Exp/Cntr=0.3,0.1

Type RM Length L Ch R = 1,11617,116,116,116
BEGIN DESCRIPTION:
Elm 01 83 11616.83
END DESCRIPTION:
XS GIS Cut Line= 3
      1577433.84      6800920.43      1578010.25      6800951.68
      1578485.92      6800911.75
#Sta/Elev= 30
  4425.8 1881.61  4477.7 1881.37  4647.3 1878.83  4677.3 1878.94  4697.4 1878.39
  4757.4 1877.80  4827.5 1877.51  4897.7 1875.37  4907.7 1875.98  4917.7 1875.77
  4927.7 1875.00  4937.7 1873.59  4947.7 1873.02  4967.8 1872.67  4985.8 1871.61
  4986.0 1871.11  4989.5 1871.11  4989.8 1871.61  5037.9 1873.52  5058.0 1873.55
  5078.1 1874.87  5098.1 1877.03  5105.0 1877.36  5110.0 1876.79  5138.3 1877.28
  5158.3 1876.62  5339.0 1878.86  5429.3 1882.26  5470.0 1884.35  5480.4 1884.42
#Mann=3,-1,0
  4425.8    0.05       0  4985.8    0.05       0  4989.8    0.05       0
Bank Sta=4985.8,4989.8
Exp/Cntr=0.3,0.1

Type RM Length L Ch R = 1,11501,70,70,70
BEGIN DESCRIPTION:
Mapping XS f4ad5dbc
END DESCRIPTION:
XS GIS Cut Line= 5
      1577348.36      6801012.26      1577775.87      6801029.62
      1577932.12      6801057.83      1578209.90      6801042.64
      1578605.95      6800992.87
#Sta/Elev= 30
  4291.9 1883.33  4759.5 1876.56  4769.7 1878.63  4779.9 1881.83  4790.0 1880.96
  4795.1 1883.90  4820.5 1877.62  4848.6 1871.90  4853.7 1872.13  4877.5 1869.12
  4891.4 1868.48  4941.5 1868.51  4964.8 1865.19  4965.1 1864.69  4968.8 1865.19
  4971.8 1866.83  5001.6 1865.20  5031.7 1866.71  5081.7 1874.86  5111.8 1876.39
  5172.0 1876.93  5202.2 1876.27  5333.2 1878.76  5403.8 1881.39  5464.2 1882.54
  5494.5 1884.33  5504.6 1884.40  5524.7 1882.21  5534.8 1882.23  5555.9 1885.32
#Mann=3,-1,0
  4291.9    0.05       0  4964.8    0.03       0  4968.8    0.05       0
Bank Sta=4964.8,4968.8
Exp/Cntr=0.3,0.1

Type RM Length L Ch R = 1,11431,87,87,87
BEGIN DESCRIPTION:
Elm 01 83 11508.637
END DESCRIPTION:
XS GIS Cut Line= 5
      1577392.85      6801042.47      1577874.66      6801118.87
      1578149.13      6801122.94      1578225.36      6801091.96
      1578583.82      6801052.90
#Sta/Elev= 30
  4331.2 1882.55  4758.6 1876.88  4768.8 1877.18  4777.7 1879.27  4782.8 1877.43
  4789.0 1880.20  4799.1 1882.90  4821.7 1883.74  4859.4 1880.75  4919.4 1881.80
  4969.4 1880.61  4989.4 1879.20  5019.4 1880.75  5079.4 1881.62  5118.0 1881.04
  5123.4 1881.74  5142.1 1879.98  5153.8 1880.83  5171.5 1880.11  5174.4 1881.26
  5178.2 1881.26  5185.5 1879.47  5205.6 1876.91  5225.8 1877.77  5252.7 1876.70
  5253.0 1876.20  5256.7 1876.70  5396.8 1879.28  5517.5 1883.79  5536.4 1881.59
#Mann=3,-1,0
  4331.2    0.05       0  5252.7    0.05       0  5256.7    0.05       0
Bank Sta=5252.7,5256.7
Exp/Cntr=0.3,0.1

Type RM Length L Ch R = 1,11344,198,198,198
BEGIN DESCRIPTION:
Mapping XS 8006c747
END DESCRIPTION:
XS GIS Cut Line= 4
      1577326.68      6801287.87      1577869.19      6801203.23
      1578318.40      6801216.25      1578641.96      6801162.33
#Sta/Elev= 30
  4264.1 1883.13  4282.6 1882.94  4291.7 1882.00  4296.7 1882.45  4313.0 1881.54
  4444.6 1880.97  4490.2 1879.57  4657.1 1877.73  4677.4 1878.31  4688.7 1877.20
  4798.8 1876.06  4829.0 1875.20  4959.0 1875.35  4997.1 1874.65  4997.3 1874.15
  5000.8 1874.15  5001.1 1874.65  5009.1 1875.16  5119.1 1875.36  5129.1 1874.92
  5159.1 1875.64  5189.1 1875.09  5269.3 1875.71  5460.8 1879.71  5502.4 1881.27
  5521.7 1882.62  5553.1 1881.37  5563.3 1881.78  5573.4 1883.45  5590.6 1884.13
#Mann=3,-1,0
  4264.1    0.05       0  4997.1    0.03       0  5001.1    0.05       0
Bank Sta=4997.1,5001.1
Exp/Cntr=0.3,0.1

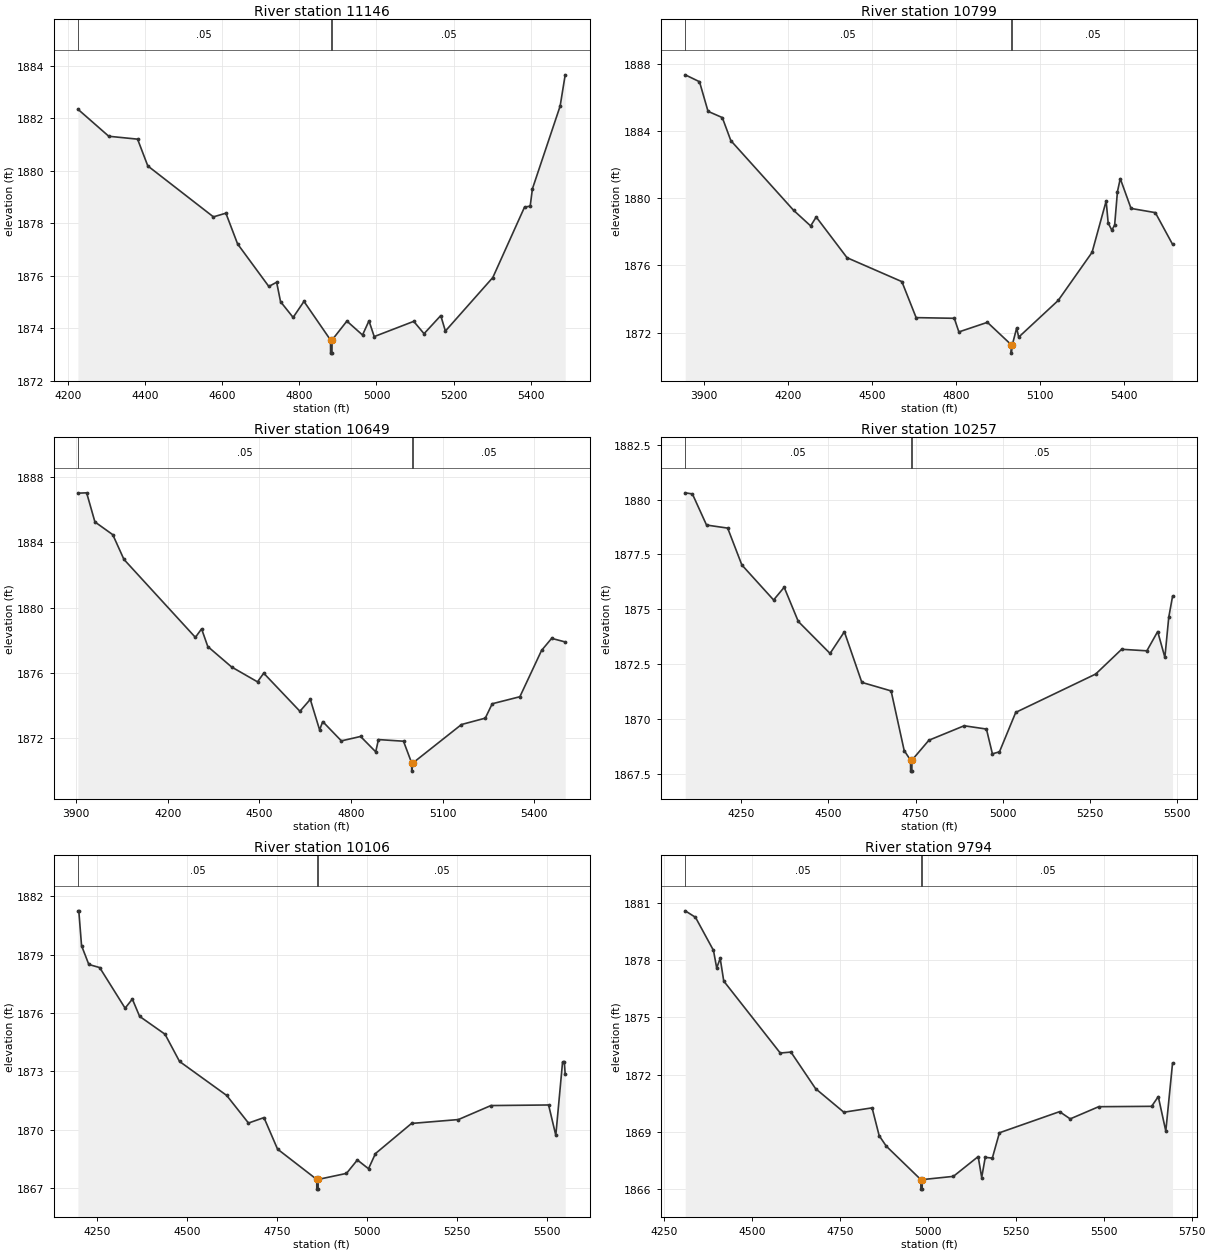
Type RM Length L Ch R = 1,11146,347,347,347
BEGIN DESCRIPTION:
Elm 01 83 11024.86
END DESCRIPTION:
XS GIS Cut Line= 3
      1577345.91      6801505.93      1578110.82      6801390.31
      1578587.78      6801282.91
#Sta/Elev= 30
  4226.4 1882.35  4306.4 1881.32  4381.0 1881.21  4407.5 1880.19  4577.5 1878.25
  4609.8 1878.39  4640.1 1877.22  4721.0 1875.60  4741.3 1875.76  4751.4 1875.02
  4784.0 1874.42  4812.1 1875.03  4880.9 1873.56  4881.1 1873.06  4884.6 1873.06
  4884.9 1873.56  4923.3 1874.28  4963.8 1873.75  4980.5 1874.29  4994.1 1873.69
  5096.5 1874.27  5123.2 1873.80  5166.5 1874.49  5178.5 1873.90  5301.4 1875.94
  5383.5 1878.62  5398.2 1878.66  5404.0 1879.32  5475.8 1882.47  5488.9 1883.66
#Mann=3,-1,0
  4226.4    0.05       0  4880.9    0.05       0  4884.9    0.05       0
Bank Sta=4880.9,4884.9
Exp/Cntr=0.3,0.1

Type RM Length L Ch R = 1,10799,150,150,150
BEGIN DESCRIPTION:
Elm 01 83 10605.324
END DESCRIPTION:
XS GIS Cut Line= 3
      1577194.99      6801840.19      1578341.12      6801624.76
      1578910.12      6801555.49
#Sta/Elev= 30
  3833.8 1887.33  3884.7 1886.92  3915.2 1885.16  3966.1 1884.79  3996.6 1883.42
  4220.5 1879.28  4281.5 1878.35  4301.3 1878.88  4411.4 1876.46  4607.1 1875.04
  4658.0 1872.90  4794.2 1872.86  4810.6 1872.05  4912.4 1872.62  4997.4 1871.29
  4997.7 1870.79  5001.4 1871.29  5016.8 1872.28  5024.1 1871.74  5165.1 1873.92
  5286.0 1876.78  5336.3 1879.83  5343.5 1878.52  5356.5 1878.10  5366.6 1878.40
  5376.6 1880.39  5386.7 1881.16  5425.1 1879.39  5511.8 1879.14  5573.2 1877.26
#Mann=3,-1,0
  3833.8    0.05       0  4997.4    0.03       0  5001.4    0.05       0
Bank Sta=4997.4,5001.4
Exp/Cntr=0.3,0.1

Type RM Length L Ch R = 1,10649,392,392,392
BEGIN DESCRIPTION:
Mapping XS 1f0f545e
END DESCRIPTION:
XS GIS Cut Line= 4
      1577226.82      6801943.25      1578133.94      6801778.32
      1578704.69      6801715.39      1578800.05      6801691.55
#Sta/Elev= 30
  3906.3 1887.00  3934.9 1887.02  3962.0 1885.24  4020.4 1884.46  4056.9 1882.95
  4290.7 1878.18  4311.0 1878.70  4331.3 1877.62  4409.2 1876.37  4494.0 1875.46
  4514.3 1875.99  4632.8 1873.66  4666.7 1874.39  4697.2 1872.52  4707.4 1873.03
  4768.4 1871.85  4831.3 1872.12  4880.8 1871.18  4889.7 1871.93  4971.7 1871.83
  4998.4 1870.50  4998.6 1870.00  5002.4 1870.50  5161.4 1872.85  5239.3 1873.24
  5262.0 1874.12  5352.5 1874.55  5423.4 1877.38  5456.5 1878.12  5500.8 1877.90
#Mann=3,-1,0
  3906.3    0.05       0  4998.4    0.05       0  5002.4    0.05       0
Bank Sta=4998.4,5002.4
Exp/Cntr=0.3,0.1

Type RM Length L Ch R = 1,10257,151,151,151
BEGIN DESCRIPTION:
Elm 01 83 10418.63
END DESCRIPTION:
XS GIS Cut Line= 3
      1577454.68      6802269.13      1578392.20      6802130.24
      1578826.17      6802019.22
#Sta/Elev= 30
  4090.3 1880.31  4110.8 1880.26  4151.3 1878.84  4211.9 1878.70  4252.4 1877.02
  4343.4 1875.42  4373.7 1876.00  4414.1 1874.44  4505.1 1872.98  4546.1 1873.97
  4596.1 1871.66  4680.0 1871.27  4717.4 1868.55  4735.6 1868.11  4735.9 1867.61
  4739.4 1867.61  4739.6 1868.11  4788.2 1869.02  4889.2 1869.68  4953.0 1869.53
  4970.1 1868.40  4990.3 1868.49  5036.9 1870.29  5265.9 1872.04  5340.3 1873.17
  5412.5 1873.10  5443.5 1873.98  5464.1 1872.80  5475.2 1874.63  5486.0 1875.58
#Mann=3,-1,0
  4090.3    0.05       0  4735.6    0.05       0  4739.6    0.05       0
Bank Sta=4735.6,4739.6
Exp/Cntr=0.3,0.1

Type RM Length L Ch R = 1,10106,312,312,312
BEGIN DESCRIPTION:
Elm 01 83 10106.163
END DESCRIPTION:
XS GIS Cut Line= 3
      1577554.98      6802388.00      1578351.44      6802286.54
      1578901.00      6802252.78
#Sta/Elev= 30
  4197.1 1881.26  4199.6 1881.26  4207.2 1879.47  4227.4 1878.50  4257.6 1878.34
  4328.2 1876.25  4348.3 1876.72  4368.5 1875.83  4439.1 1874.91  4479.4 1873.51
  4610.4 1871.76  4670.9 1870.34  4713.9 1870.62  4751.6 1869.00  4860.5 1867.44
  4860.7 1866.94  4864.2 1866.94  4864.5 1867.44  4943.1 1867.75  4973.3 1868.44
  5004.3 1867.99  5023.6 1868.77  5123.8 1870.32  5254.0 1870.52  5344.2 1871.24
  5504.5 1871.27  5524.5 1869.71  5543.3 1873.48  5548.3 1873.46  5550.6 1872.84
#Mann=3,-1,0
  4197.1    0.05       0  4860.5    0.05       0  4864.5    0.05       0
Bank Sta=4860.5,4864.5
Exp/Cntr=0.3,0.1

Type RM Length L Ch R = 1,9794,126,126,126
BEGIN DESCRIPTION:
Elm 01 83 9794.04
END DESCRIPTION:
XS GIS Cut Line= 3
      1577576.00      6802599.94      1578263.90      6802537.01
      1578954.02      6802458.88
#Sta/Elev= 30
  4310.3 1880.60  4339.4 1880.26  4390.6 1878.52  4399.7 1877.60  4409.7 1878.10
  4419.8 1876.91  4580.4 1873.13  4610.8 1873.18  4680.8 1871.26  4761.2 1870.02
  4841.5 1870.25  4861.6 1868.79  4881.7 1868.24  4980.1 1866.48  4980.3 1865.98
  4983.8 1865.98  4984.1 1866.48  5072.6 1866.65  5143.1 1867.69  5153.1 1866.59
  5163.2 1867.65  5183.3 1867.61  5203.5 1868.94  5374.5 1870.05  5404.7 1869.67
  5485.7 1870.31  5636.2 1870.33  5655.1 1870.84  5676.5 1869.03  5695.6 1872.59
#Mann=3,-1,0
  4310.3    0.05       0  4980.1    0.03       0  4984.1    0.05       0
Bank Sta=4980.1,4984.1
Exp/Cntr=0.3,0.1

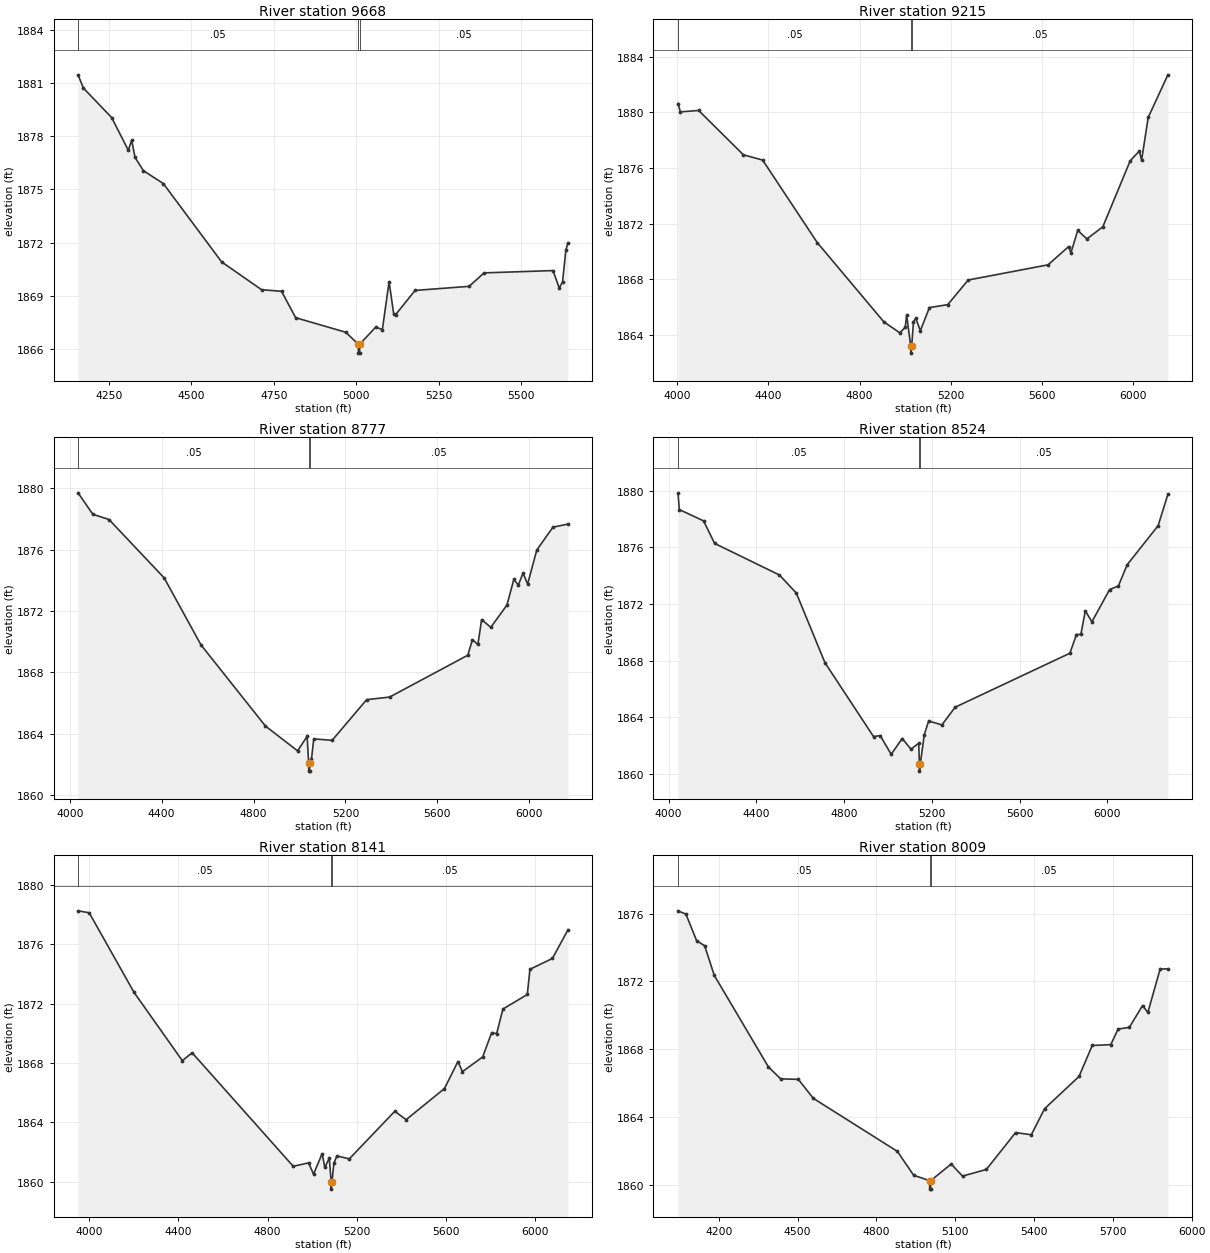
Type RM Length L Ch R = 1,9668,453,453,453
BEGIN DESCRIPTION:
Elm 01 83 9617.752
END DESCRIPTION:
XS GIS Cut Line= 3
      1577514.74      6802765.89      1578173.00      6802655.06
      1578981.24      6802535.88
#Sta/Elev= 30
  4156.8 1881.47  4173.2 1880.72  4258.5 1879.06  4309.2 1877.21  4319.3 1877.78
  4329.5 1876.81  4354.8 1876.06  4415.4 1875.33  4591.9 1870.91  4713.0 1869.34
  4773.5 1869.25  4816.2 1867.76  4967.9 1866.94  5006.3 1866.26  5006.5 1865.76
  5010.0 1865.76  5010.3 1866.26  5058.8 1867.23  5079.0 1867.09  5099.3 1869.79
  5113.5 1867.95  5119.5 1867.94  5178.1 1869.30  5341.9 1869.53  5387.1 1870.29
  5596.1 1870.42  5614.8 1869.44  5624.9 1869.77  5635.0 1871.57  5641.3 1871.99
#Mann=3,-1,0
  4156.8    0.05       0  5006.3    0.05       0  5010.3    0.05       0
Bank Sta=5006.3,5010.3
Exp/Cntr=0.3,0.1

Type RM Length L Ch R = 1,9215,438,438,438
BEGIN DESCRIPTION:
Elm 01 83 9140.956
END DESCRIPTION:
XS GIS Cut Line= 3
      1577364.55      6803050.55      1578358.59      6802989.65
      1579510.18      6802993.26
#Sta/Elev= 30
  4004.1 1880.63  4014.6 1880.03  4094.7 1880.13  4290.6 1876.95  4375.2 1876.57
  4614.4 1870.65  4906.2 1864.96  4976.4 1864.17  5000.0 1864.56  5006.4 1865.43
  5024.4 1863.21  5024.7 1862.71  5028.4 1863.21  5036.4 1864.96  5046.4 1865.22
  5066.4 1864.32  5106.4 1865.98  5186.4 1866.19  5276.4 1867.96  5626.4 1869.05
  5716.4 1870.36  5726.4 1869.90  5756.4 1871.52  5796.4 1870.91  5866.4 1871.78
  5986.4 1876.52  6026.4 1877.22  6036.4 1876.57  6065.3 1879.63  6151.6 1882.69
#Mann=3,-1,0
  4004.1    0.05       0  5024.4    0.05       0  5028.4    0.05       0
Bank Sta=5024.4,5028.4
Exp/Cntr=0.3,0.1

Type RM Length L Ch R = 1,8777,253,253,253
BEGIN DESCRIPTION:
Elm 01 83 8661.517
END DESCRIPTION:
XS GIS Cut Line= 3
      1577450.49      6803394.30      1578412.84      6803334.60
      1579580.36      6803271.93
#Sta/Elev= 30
  4035.8 1879.70  4100.4 1878.30  4170.6 1877.96  4411.0 1874.15  4571.3 1869.78
  4851.9 1864.49  4992.1 1862.87  5033.5 1863.82  5040.2 1862.05  5040.5 1861.55
  5044.0 1861.55  5044.2 1862.05  5052.2 1862.31  5062.3 1863.65  5142.4 1863.56
  5292.6 1866.21  5392.7 1866.38  5733.2 1869.11  5753.2 1870.12  5777.2 1869.81
  5793.3 1871.43  5833.4 1870.93  5903.5 1872.38  5933.5 1874.05  5953.5 1873.69
  5973.6 1874.47  5993.6 1873.75  6033.6 1875.97  6103.8 1877.46  6169.2 1877.66
#Mann=3,-1,0
  4035.8    0.05       0  5040.2    0.05       0  5044.2    0.05       0
Bank Sta=5040.2,5044.2
Exp/Cntr=0.3,0.1

Type RM Length L Ch R = 1,8524,383,383,383
BEGIN DESCRIPTION:
Elm 01 83 8168.23
END DESCRIPTION:
XS GIS Cut Line= 3
      1577409.08      6803644.64      1578254.60      6803549.40
      1579629.37      6803401.24
#Sta/Elev= 30
  4042.8 1879.84  4048.8 1878.66  4159.5 1877.86  4209.8 1876.27  4505.4 1874.04
  4582.1 1872.77  4712.9 1867.85  4934.3 1862.64  4964.5 1862.71  5014.8 1861.39
  5065.1 1862.50  5105.3 1861.75  5140.3 1862.17  5143.5 1860.70  5143.8 1860.20
  5147.5 1860.70  5165.6 1862.77  5185.7 1863.74  5246.1 1863.46  5306.4 1864.71
  5829.5 1868.52  5859.6 1869.84  5879.7 1869.85  5899.9 1871.51  5930.0 1870.74
  6010.5 1873.01  6050.7 1873.27  6091.0 1874.77  6231.8 1877.52  6276.4 1879.74
#Mann=3,-1,0
  4042.8    0.05       0  5143.5    0.05       0  5147.5    0.05       0
Bank Sta=5143.5,5147.5
Exp/Cntr=0.3,0.1

Type RM Length L Ch R = 1,8141,132,132,132
BEGIN DESCRIPTION:
Mapping XS b1a739bf
END DESCRIPTION:
XS GIS Cut Line= 4
      1577435.15      6803928.93      1578251.13      6803848.63
      1579010.68      6803722.77      1579613.94      6803638.13
#Sta/Elev= 30
  3949.1 1878.25  3999.2 1878.12  4200.2 1872.76  4417.1 1868.15  4461.4 1868.68
  4914.9 1861.03  4983.9 1861.26  5006.1 1860.50  5044.9 1861.88  5056.8 1860.95
  5077.0 1861.58  5085.2 1859.99  5085.4 1859.49  5089.2 1859.99  5097.3 1861.22
  5110.9 1861.73  5166.8 1861.53  5371.0 1864.74  5421.7 1864.17  5593.8 1866.27
  5654.4 1868.09  5674.6 1867.41  5765.4 1868.40  5805.8 1870.04  5828.1 1869.97
  5856.3 1871.63  5965.7 1872.61  5977.5 1874.31  6078.5 1875.04  6148.1 1876.97
#Mann=3,-1,0
  3949.1    0.05       0  5085.2    0.05       0  5089.2    0.05       0
Bank Sta=5085.2,5089.2
Exp/Cntr=0.3,0.1

Type RM Length L Ch R = 1,8009,524,524,524
BEGIN DESCRIPTION:
Elm 01 83 8009.25
END DESCRIPTION:
XS GIS Cut Line= 3
      1577564.93      6804085.05      1578507.61      6803934.01
      1579410.67      6803819.50
#Sta/Elev= 30
  4044.5 1876.17  4075.0 1875.97  4115.5 1874.40  4145.9 1874.11  4182.6 1872.36
  4388.9 1866.95  4435.6 1866.25  4502.7 1866.22  4559.6 1865.10  4879.6 1861.97
  4941.6 1860.56  5002.4 1860.24  5002.7 1859.74  5006.2 1859.74  5006.4 1860.24
  5084.5 1861.22  5127.6 1860.51  5218.3 1860.90  5329.8 1863.08  5389.7 1862.95
  5440.1 1864.49  5571.1 1866.39  5621.5 1868.22  5692.1 1868.27  5720.0 1869.19
  5762.7 1869.29  5813.1 1870.58  5833.2 1870.17  5880.1 1872.74  5909.5 1872.74
#Mann=3,-1,0
  4044.5    0.05       0  5002.4    0.05       0  5006.4    0.05       0
Bank Sta=5002.4,5006.4
Exp/Cntr=0.3,0.1

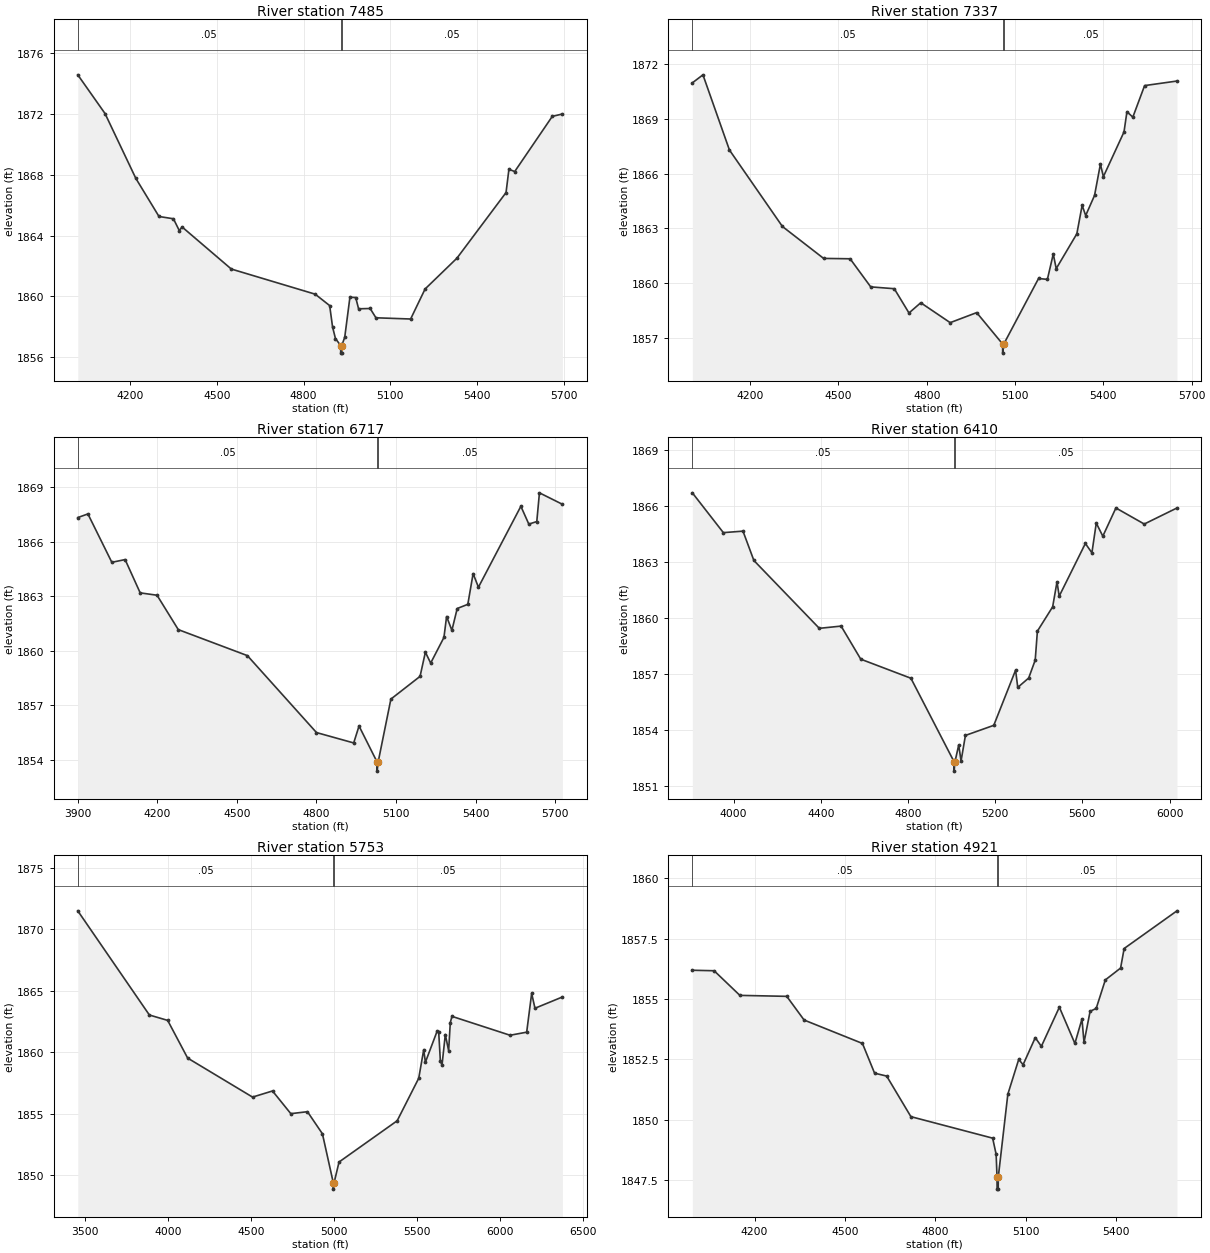
Type RM Length L Ch R = 1,7485,148,148,148
BEGIN DESCRIPTION:
Elm 01 83 7695.591
END DESCRIPTION:
XS GIS Cut Line= 3
      1577674.24      6804338.53      1578653.48      6804385.86
      1579349.99      6804361.97
#Sta/Elev= 30
  4018.2 1874.55  4112.5 1872.01  4219.2 1867.75  4299.3 1865.25  4349.3 1865.10
  4369.4 1864.33  4379.4 1864.56  4549.6 1861.80  4839.9 1860.15  4890.0 1859.40
  4900.0 1858.00  4910.0 1857.24  4928.0 1856.78  4928.3 1856.28  4931.8 1856.28
  4932.0 1856.78  4942.2 1857.33  4960.1 1859.95  4980.1 1859.93  4990.1 1859.19
  5030.1 1859.21  5050.1 1858.60  5170.2 1858.52  5220.2 1860.49  5330.3 1862.51
  5500.4 1866.82  5510.4 1868.35  5530.4 1868.20  5660.4 1871.82  5695.5 1871.98
#Mann=3,-1,0
  4018.2    0.05       0  4928.0    0.05       0  4932.0    0.05       0
Bank Sta=4928,4932
Exp/Cntr=0.3,0.1

Type RM Length L Ch R = 1,7337,620,620,620
BEGIN DESCRIPTION:
Elm 01 83 7198.708
END DESCRIPTION:
XS GIS Cut Line= 3
      1577709.01      6804522.56      1578705.30      6804517.83
      1579354.84      6804488.70
#Sta/Elev= 30
  4003.7 1870.97  4039.7 1871.41  4129.7 1867.29  4309.7 1863.10  4449.7 1861.35
  4539.7 1861.33  4609.7 1859.79  4689.7 1859.69  4739.7 1858.36  4779.7 1858.92
  4879.7 1857.83  4969.7 1858.38  5057.8 1856.66  5058.0 1856.16  5061.8 1856.66
  5179.9 1860.25  5209.9 1860.20  5229.9 1861.59  5239.9 1860.79  5310.0 1862.70
  5328.0 1864.26  5340.0 1863.70  5370.1 1864.80  5390.1 1866.52  5400.1 1865.83
  5470.2 1868.28  5480.2 1869.39  5500.2 1869.09  5540.2 1870.82  5650.2 1871.07
#Mann=3,-1,0
  4003.7    0.05       0  5057.8    0.05       0  5061.8    0.05       0
Bank Sta=5057.8,5061.8
Exp/Cntr=0.3,0.1

Type RM Length L Ch R = 1,6717,307,307,307
BEGIN DESCRIPTION:
Elm 01 83 6716.78
END DESCRIPTION:
XS GIS Cut Line= 3
      1577706.84      6804848.08      1578807.52      6804917.52
      1579531.62      6804924.45
#Sta/Elev= 30
  3900.2 1867.33  3938.4 1867.53  4028.6 1864.87  4078.7 1865.02  4135.5 1863.19
  4199.0 1863.06  4279.1 1861.17  4539.6 1859.74  4800.1 1855.51  4940.4 1854.94
  4960.5 1855.87  5028.6 1853.89  5028.8 1853.39  5032.6 1853.89  5080.6 1857.35
  5190.6 1858.60  5210.6 1859.93  5230.6 1859.33  5280.6 1860.74  5290.6 1861.89
  5310.6 1861.13  5330.6 1862.33  5370.6 1862.56  5390.6 1864.25  5410.6 1863.50
  5570.6 1867.95  5600.6 1866.97  5630.6 1867.11  5640.6 1868.69  5727.2 1868.06
#Mann=3,-1,0
  3900.2    0.05       0  5028.6    0.05       0  5032.6    0.05       0
Bank Sta=5028.6,5032.6
Exp/Cntr=0.3,0.1

Type RM Length L Ch R = 1,6410,657,657,657
BEGIN DESCRIPTION:
Elm 01 83 6410.16
END DESCRIPTION:
XS GIS Cut Line= 3
      1577522.84      6805230.02      1578713.77      6805191.83
      1579745.05      6805226.55
#Sta/Elev= 30
  3810.9 1866.69  3953.1 1864.56  4043.2 1864.64  4093.2 1863.07  4393.4 1859.44
  4493.4 1859.56  4583.5 1857.79  4813.6 1856.77  5011.7 1852.30  5011.9 1851.80
  5015.7 1852.30  5033.0 1853.20  5043.7 1852.34  5063.7 1853.71  5193.8 1854.25
  5293.8 1857.20  5303.8 1856.28  5353.9 1856.78  5383.9 1857.74  5393.9 1859.29
  5463.9 1860.59  5483.9 1861.93  5493.9 1861.16  5614.0 1863.98  5644.0 1863.48
  5664.0 1865.07  5694.1 1864.37  5754.1 1865.88  5884.2 1865.02  6034.3 1865.88
#Mann=3,-1,0
  3810.9    0.05       0  5011.7    0.05       0  5015.7    0.05       0
Bank Sta=5011.7,5015.7
Exp/Cntr=0.3,0.1

Type RM Length L Ch R = 1,5753,832,832,832
BEGIN DESCRIPTION:
Elm 01 83 5753.087
END DESCRIPTION:
XS GIS Cut Line= 3
      1577214.61      6805591.13      1578755.42      6805703.44
      1580130.20      6805750.85
#Sta/Elev= 30
  3455.1 1871.52  3886.6 1863.03  3996.9 1862.59  4117.2 1859.52  4508.3 1856.34
  4628.6 1856.84  4738.9 1854.99  4839.2 1855.15  4929.4 1853.35  4995.2 1849.34
  4995.5 1848.84  4999.3 1849.34  5029.6 1851.05  5379.8 1854.41  5509.9 1857.88
  5539.9 1860.21  5549.9 1859.18  5620.0 1861.69  5630.0 1861.68  5640.0 1859.31
  5650.0 1858.94  5670.0 1861.44  5690.0 1860.12  5700.0 1862.41  5710.0 1862.92
  6060.2 1861.38  6160.3 1861.63  6190.3 1864.79  6210.3 1863.58  6375.6 1864.50
#Mann=3,-1,0
  3455.1    0.05       0  4995.2    0.05       0  4999.3    0.05       0
Bank Sta=4995.2,4999.3
Exp/Cntr=0.3,0.1

Type RM Length L Ch R = 1,4921,452,452,452
BEGIN DESCRIPTION:
Elm 01 83 4921.14
END DESCRIPTION:
XS GIS Cut Line= 3
      1578153.15      6806207.68      1579156.62      6806113.93
      1579750.17      6806027.16
#Sta/Elev= 30
  3993.6 1856.19  4065.8 1856.17  4151.3 1855.15  4306.8 1855.11  4364.3 1854.13
  4557.9 1853.16  4598.1 1851.93  4638.2 1851.81  4718.6 1850.13  4989.8 1849.24
  5001.4 1848.57  5004.3 1847.63  5004.6 1847.13  5008.2 1847.13  5008.5 1847.63
  5040.2 1851.06  5076.3 1852.50  5090.8 1852.28  5131.2 1853.40  5151.4 1853.04
  5211.1 1854.66  5262.6 1853.16  5286.1 1854.17  5292.9 1853.20  5313.1 1854.49
  5333.3 1854.61  5363.6 1855.79  5414.2 1856.28  5426.0 1857.09  5601.3 1858.65
#Mann=3,-1,0
  3993.6    0.05       0  5004.3    0.05       0  5008.5    0.05       0
Bank Sta=5004.3,5008.5
Exp/Cntr=0.3,0.1