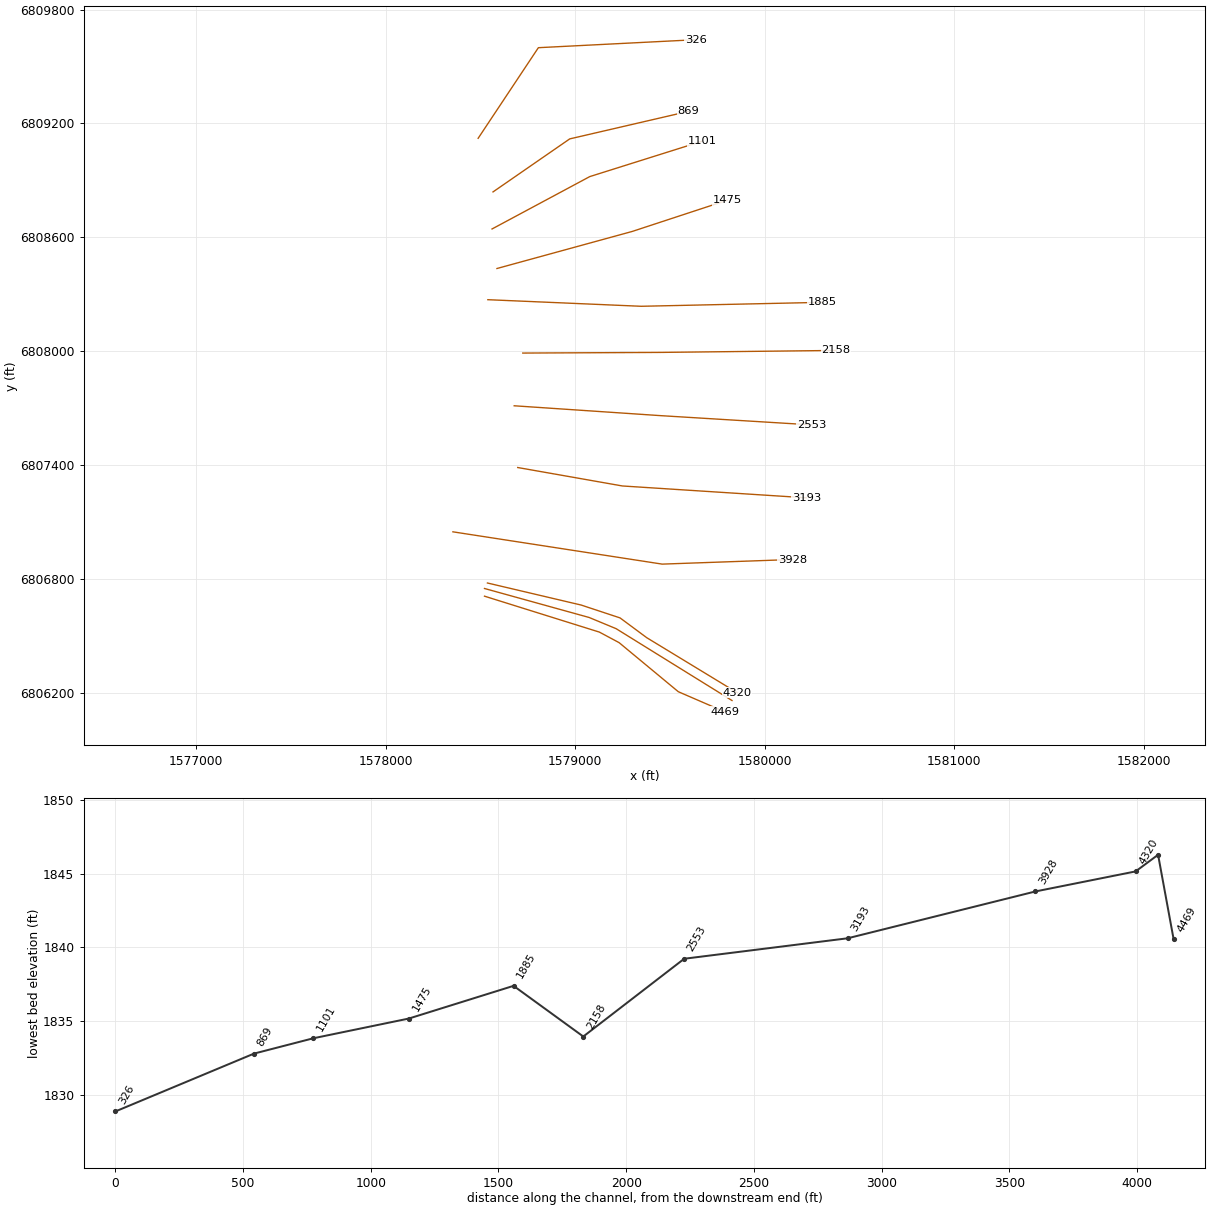
HEC-RAS study Elm 01 83.prj: Elm 01 83 Base Level Engineering

--- Elm 01 83.g01 (geometry) --- (continued)

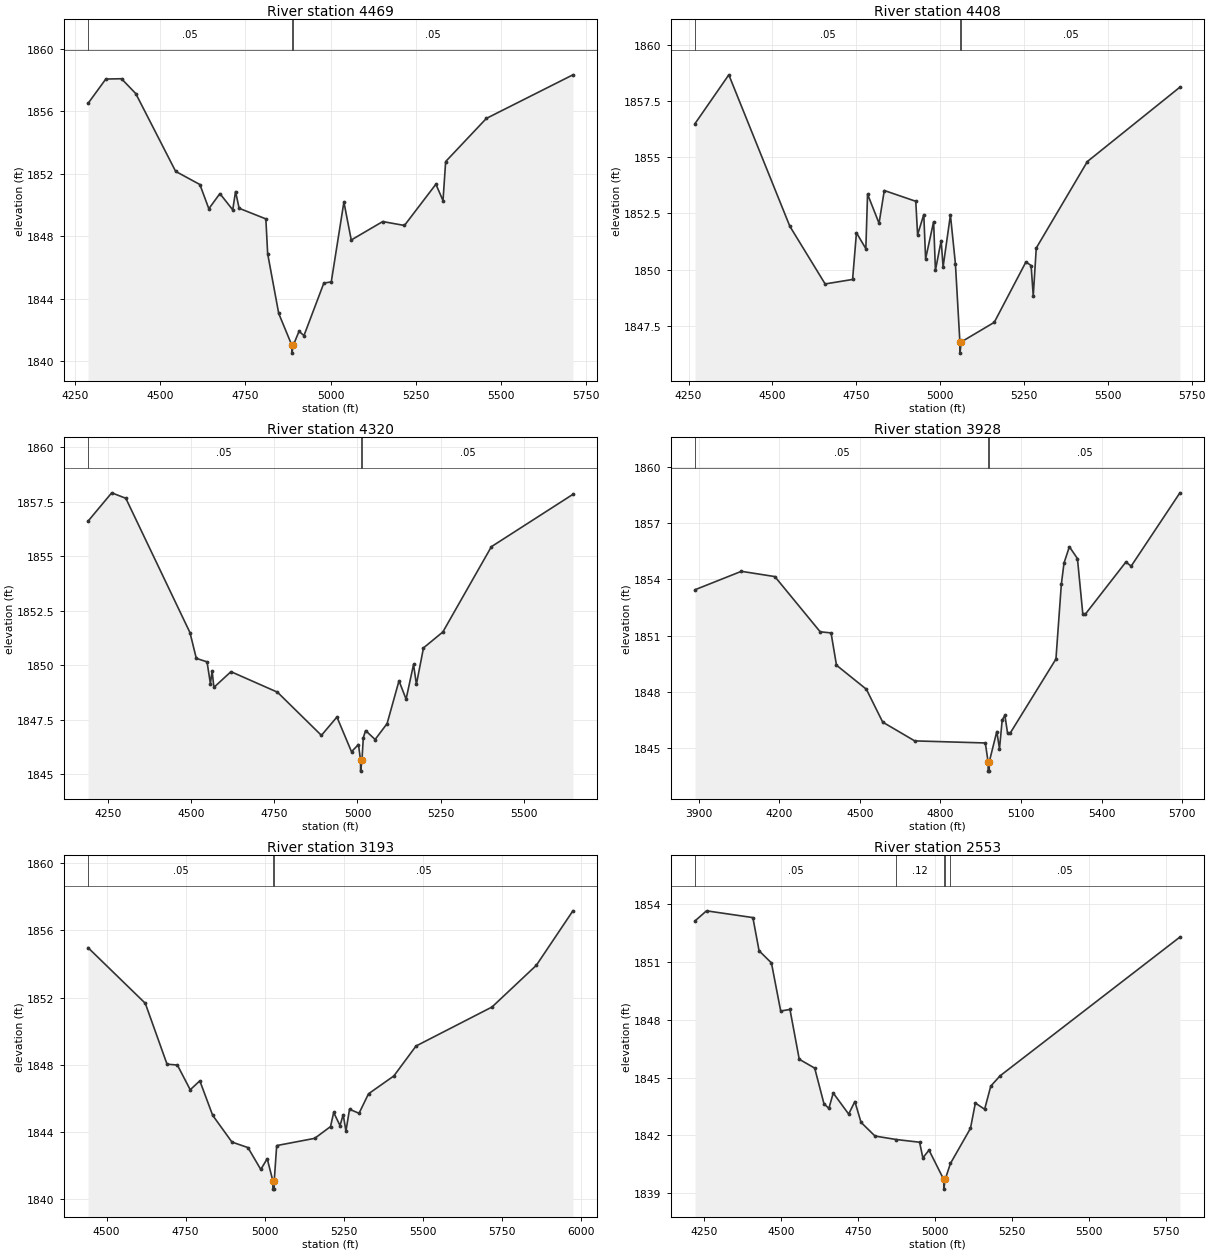
Type RM Length L Ch R = 1,4469,61,61,61
BEGIN DESCRIPTION:
Mapping XS 14802b16
END DESCRIPTION:
XS GIS Cut Line= 5
      1578521.12      6806708.87      1579127.00      6806519.64
      1579231.16      6806464.08      1579543.66      6806205.40
      1579788.46      6806099.50
#Sta/Elev= 30
  4287.2 1856.51  4339.4 1858.07  4385.6 1858.09  4427.5 1857.14  4544.8 1852.16
  4616.0 1851.32  4642.3 1849.77  4674.8 1850.74  4712.5 1849.70  4720.8 1850.87
  4731.3 1849.80  4809.9 1849.12  4815.2 1846.89  4847.7 1843.07  4886.3 1841.03
  4886.6 1840.53  4890.5 1841.03  4907.4 1841.93  4921.9 1841.65  4980.3 1845.01
  5002.2 1845.09  5039.3 1850.20  5060.9 1847.77  5153.4 1848.95  5217.2 1848.70
  5309.7 1851.34  5330.6 1850.29  5338.4 1852.79  5458.0 1855.55  5712.4 1858.34
#Mann=3,-1,0
  4287.2    0.05       0  4886.3    0.05       0  4890.5    0.05       0
Bank Sta=4886.3,4890.5
Exp/Cntr=0.3,0.1

Type RM Length L Ch R = 1,4408,88,88,88
BEGIN DESCRIPTION:
Elm 01 83 4407.69
END DESCRIPTION:
XS GIS Cut Line= 4
      1578521.16      6806749.36      1579073.29      6806596.57
      1579215.65      6806537.54      1579826.75      6806159.08
#Sta/Elev= 30
  4269.3 1856.50  4370.0 1858.67  4551.9 1851.93  4657.2 1849.36  4739.1 1849.56
  4750.6 1851.64  4778.6 1850.93  4783.7 1853.36  4818.0 1852.06  4833.6 1853.52
  4927.5 1853.04  4932.9 1851.55  4951.4 1852.45  4956.8 1850.48  4980.7 1852.13
  4986.1 1849.97  5003.2 1851.29  5009.0 1850.12  5030.8 1852.43  5045.7 1850.26
  5059.0 1846.78  5059.2 1846.28  5063.2 1846.78  5161.5 1847.65  5256.0 1850.34
  5271.4 1850.18  5277.8 1848.83  5286.8 1850.96  5439.2 1854.81  5715.1 1858.12
#Mann=3,-1,0
  4269.3    0.05       0  5059.0    0.05       0  5063.2    0.05       0
Bank Sta=5059,5063.2
Exp/Cntr=0.3,0.1

Type RM Length L Ch R = 1,4320,392,392,392
BEGIN DESCRIPTION:
Mapping XS 3b31ecfb
END DESCRIPTION:
XS GIS Cut Line= 5
      1578536.68      6806778.33      1579031.51      6806662.00
      1579236.37      6806594.29      1579377.00      6806490.13
      1579854.46      6806200.17
#Sta/Elev= 30
  4189.9 1856.61  4261.1 1857.91  4303.5 1857.66  4496.4 1851.50  4515.4 1850.32
  4547.7 1850.16  4557.8 1849.16  4562.9 1849.75  4568.3 1848.99  4619.6 1849.71
  4759.3 1848.77  4891.5 1846.79  4938.2 1847.63  4982.0 1846.04  5002.9 1846.37
  5009.2 1845.65  5009.4 1845.15  5013.4 1845.65  5017.5 1846.68  5024.3 1847.01
  5053.0 1846.60  5089.0 1847.33  5124.8 1849.29  5146.1 1848.45  5168.5 1850.04
  5177.1 1849.13  5198.4 1850.80  5256.6 1851.53  5402.5 1855.44  5647.6 1857.84
#Mann=3,-1,0
  4189.9    0.05       0  5009.2    0.05       0  5013.4    0.05       0
Bank Sta=5009.2,5013.4
Exp/Cntr=0.3,0.1

Type RM Length L Ch R = 1,3928,735,735,735
BEGIN DESCRIPTION:
Elm 01 83 3928.36
END DESCRIPTION:
XS GIS Cut Line= 3
      1578354.50      6807047.97      1579458.70      6806877.82
      1580146.23      6806902.13
#Sta/Elev= 30
  3886.5 1853.45  4059.0 1854.43  4183.6 1854.15  4352.4 1851.21  4392.9 1851.15
  4413.1 1849.43  4524.4 1848.15  4585.2 1846.40  4704.3 1845.40  4967.2 1845.29
  4977.5 1844.29  4977.9 1843.79  4981.7 1843.79  4982.0 1844.29  5010.0 1845.90
  5020.0 1844.98  5030.1 1846.52  5040.1 1846.76  5050.1 1845.81  5060.1 1845.82
  5230.2 1849.76  5250.2 1853.73  5260.2 1854.87  5280.2 1855.74  5310.2 1855.11
  5330.2 1852.16  5340.2 1852.16  5490.3 1854.92  5510.4 1854.71  5691.7 1858.61
#Mann=3,-1,0
  3886.5    0.05       0  4977.5    0.05       0  4982.0    0.05       0
Bank Sta=4977.5,4982
Exp/Cntr=0.3,0.1

Type RM Length L Ch R = 1,3193,640,640,640
BEGIN DESCRIPTION:
Elm 01 83 3193.3
END DESCRIPTION:
XS GIS Cut Line= 3
      1578696.54      6807386.85      1579248.64      6807289.63
      1580220.44      6807227.16
#Sta/Elev= 30
  4441.4 1854.97  4622.6 1851.66  4691.4 1848.04  4724.1 1847.99  4764.8 1846.52
  4795.2 1847.05  4835.8 1845.00  4896.8 1843.41  4947.5 1843.08  4988.1 1841.78
  5008.4 1842.42  5026.2 1841.11  5026.5 1840.61  5030.4 1840.61  5030.7 1841.11
  5038.4 1843.20  5158.7 1843.63  5208.8 1844.33  5218.8 1845.17  5238.8 1844.39
  5248.9 1845.04  5257.5 1844.06  5268.9 1845.36  5299.0 1845.12  5329.0 1846.28
  5409.2 1847.34  5479.3 1849.12  5719.8 1851.44  5860.1 1853.92  5975.8 1857.16
#Mann=3,-1,0
  4441.4    0.05       0  5026.2    0.05       0  5030.7    0.05       0
Bank Sta=5026.2,5030.7
Exp/Cntr=0.3,0.1

Type RM Length L Ch R = 1,2553,395,395,395
BEGIN DESCRIPTION:
Elm 01 83 2552.5
END DESCRIPTION:
XS GIS Cut Line= 3
      1578677.80      6807712.20      1579452.11      6807660.11
      1580247.26      6807611.50
#Sta/Elev= 30
  4221.3 1853.12  4258.6 1853.64  4408.9 1853.29  4429.0 1851.57  4469.1 1850.94
  4499.1 1848.45  4529.2 1848.53  4559.3 1845.95  4609.4 1845.49  4639.4 1843.65
  4655.4 1843.40  4669.5 1844.20  4719.6 1843.11  4739.7 1843.76  4759.7 1842.68
  4805.1 1841.97  4874.3 1841.79  4949.7 1841.65  4960.2 1840.84  4980.2 1841.24
  5028.0 1839.72  5028.4 1839.22  5032.6 1839.72  5049.7 1840.55  5114.7 1842.37
  5130.5 1843.68  5160.6 1843.36  5180.6 1844.56  5210.7 1845.09  5794.0 1852.28
#Mann=5,-1,0
  4221.3    0.05       0  4874.3    0.12       0  5028.0    0.07       0
  5032.6    0.12       0  5049.7    0.05       0
Bank Sta=5028,5032.6
Exp/Cntr=0.3,0.1

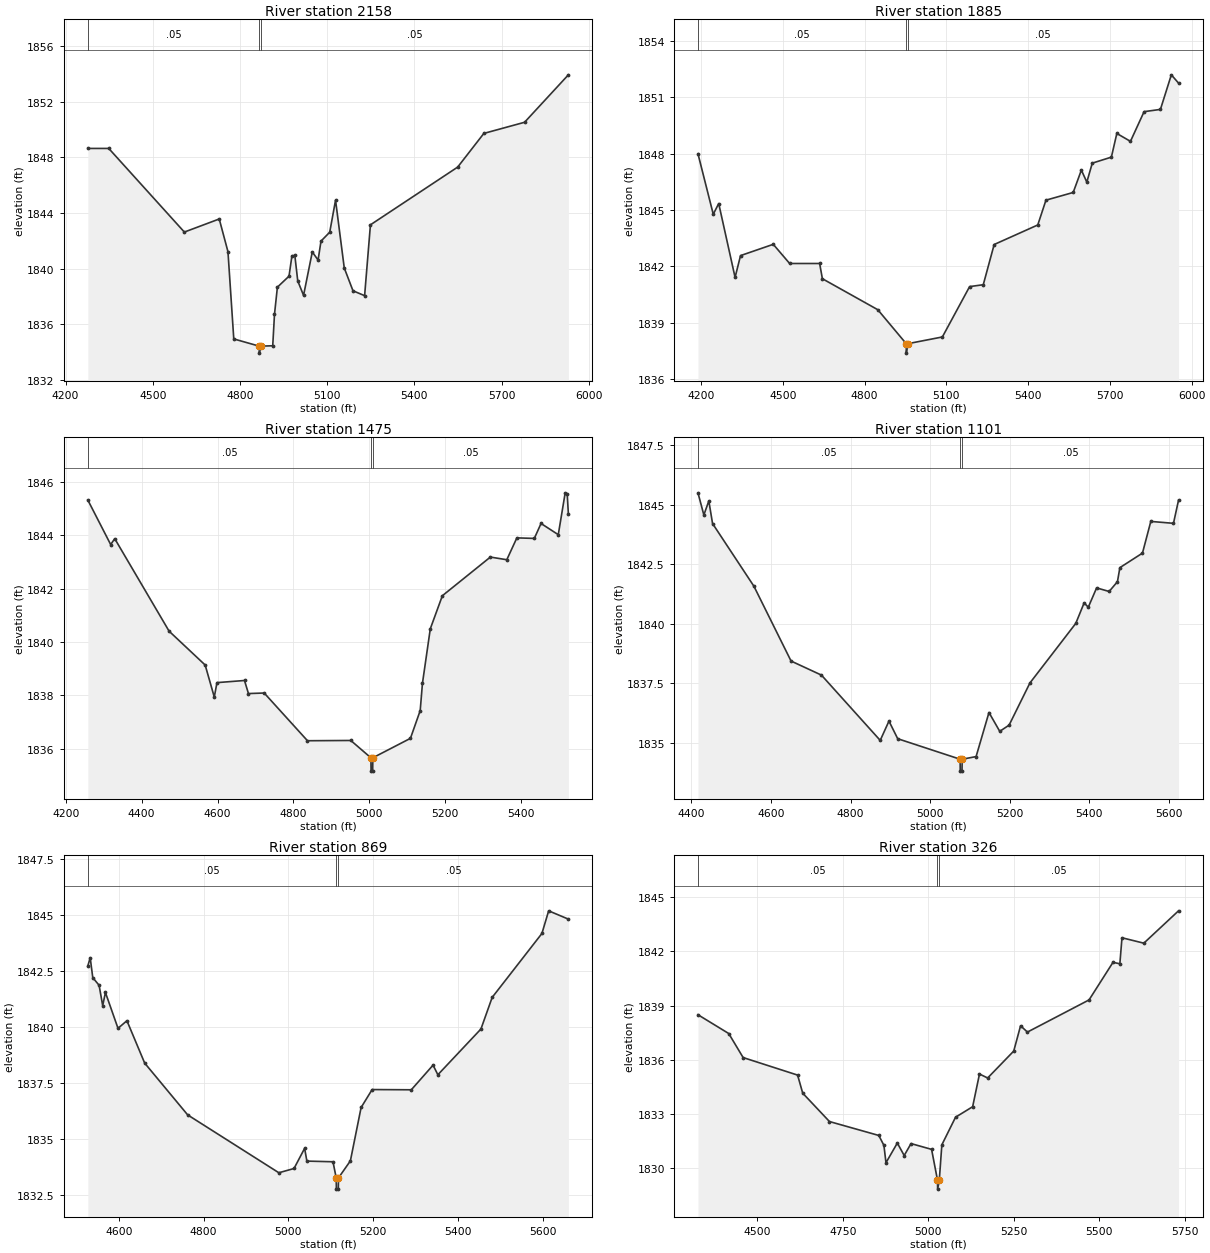
Type RM Length L Ch R = 1,2158,273,273,273
BEGIN DESCRIPTION:
Elm 01 83 2157.71
END DESCRIPTION:
XS GIS Cut Line= 3
      1578722.99      6807989.98      1579452.11      6807993.45
      1580375.72      6808003.86
#Sta/Elev= 30
  4276.7 1848.65  4348.7 1848.65  4608.7 1842.64  4728.7 1843.58  4758.7 1841.23
  4778.7 1834.96  4866.4 1834.44  4866.7 1833.94  4871.0 1834.44  4912.7 1834.47
  4918.7 1836.72  4928.7 1838.68  4968.7 1839.47  4978.7 1840.93  4988.7 1840.96
  4998.7 1839.13  5018.7 1838.09  5048.7 1841.21  5068.7 1840.63  5078.7 1841.99
  5108.7 1842.63  5128.7 1844.93  5158.7 1840.06  5188.7 1838.42  5228.7 1838.07
  5248.7 1843.16  5548.8 1847.31  5638.8 1849.73  5778.8 1850.53  5929.5 1853.94
#Mann=3,-1,0
  4276.7    0.05       0  4866.4    0.05       0  4871.0    0.05       0
Bank Sta=4866.4,4871
Exp/Cntr=0.3,0.1

Type RM Length L Ch R = 1,1885,410,410,410
BEGIN DESCRIPTION:
Elm 01 83 1885.15
END DESCRIPTION:
XS GIS Cut Line= 3
      1578538.95      6808271.22      1579347.94      6808236.50
      1580301.38      6808257.31
#Sta/Elev= 30
  4188.5 1847.99  4244.6 1844.77  4264.6 1845.34  4324.7 1841.41  4344.7 1842.57
  4464.8 1843.17  4524.9 1842.15  4635.0 1842.15  4645.0 1841.34  4848.4 1839.69
  4952.8 1837.88  4953.2 1837.38  4957.7 1837.88  5085.3 1838.24  5185.3 1840.92
  5235.4 1841.02  5275.4 1843.16  5435.4 1844.20  5465.4 1845.52  5565.4 1845.93
  5595.4 1847.12  5615.4 1846.48  5635.4 1847.49  5705.5 1847.81  5725.5 1849.07
  5775.5 1848.65  5825.5 1850.23  5885.5 1850.35  5925.5 1852.19  5951.9 1851.75
#Mann=3,-1,0
  4188.5    0.05       0  4952.8    0.05       0  4957.7    0.05       0
Bank Sta=4952.8,4957.7
Exp/Cntr=0.3,0.1

Type RM Length L Ch R = 1,1475,374,374,374
BEGIN DESCRIPTION:
Elm 01 83 1475.26
END DESCRIPTION:
XS GIS Cut Line= 3
      1578586.90      6808435.57      1579300.49      6808630.89
      1579800.24      6808794.87
#Sta/Elev= 30
  4258.4 1845.33  4318.6 1843.66  4329.3 1843.88  4472.5 1840.41  4567.5 1839.14
  4591.5 1837.94  4598.6 1838.48  4671.1 1838.56  4681.5 1838.07  4723.0 1838.09
  4837.0 1836.30  4951.1 1836.31  5004.1 1835.66  5004.5 1835.16  5008.7 1835.16
  5009.1 1835.66  5108.2 1836.39  5133.9 1837.43  5139.8 1838.45  5160.5 1840.50
  5192.3 1841.74  5318.7 1843.19  5362.0 1843.09  5388.5 1843.91  5434.5 1843.89
  5452.2 1844.45  5497.6 1844.03  5515.8 1845.60  5521.1 1845.56  5524.2 1844.81
#Mann=3,-1,0
  4258.4    0.05       0  5004.1    0.05       0  5009.1    0.05       0
Bank Sta=5004.1,5009.1
Exp/Cntr=0.3,0.1

Type RM Length L Ch R = 1,1101,232,232,232
BEGIN DESCRIPTION:
Elm 01 83 1100.58
END DESCRIPTION:
XS GIS Cut Line= 3
      1578560.93      6808643.93      1579076.53      6808919.95
      1579671.48      6809107.01
#Sta/Elev= 30
  4416.4 1845.50  4431.2 1844.57  4443.7 1845.16  4453.1 1844.21  4557.1 1841.58
  4650.5 1838.44  4726.9 1837.85  4874.7 1835.11  4896.7 1835.92  4918.7 1835.18
  5075.6 1834.32  5076.0 1833.82  5080.4 1833.82  5080.8 1834.32  5115.8 1834.43
  5148.2 1836.28  5175.3 1835.49  5198.8 1835.75  5251.2 1837.52  5366.5 1840.02
  5387.5 1840.88  5398.0 1840.70  5418.9 1841.51  5450.4 1841.36  5471.3 1841.77
  5477.4 1842.36  5534.2 1842.97  5555.2 1844.30  5612.2 1844.22  5624.9 1845.19
#Mann=3,-1,0
  4416.4    0.05       0  5075.6    0.05       0  5080.8    0.05       0
Bank Sta=5075.6,5080.8
Exp/Cntr=0.3,0.1

Type RM Length L Ch R = 1,869,543,543,543
BEGIN DESCRIPTION:
Elm 01 83 739.78
END DESCRIPTION:
XS GIS Cut Line= 3
      1578566.15      6808839.25      1578970.75      6809118.60
      1579595.84      6809263.35
#Sta/Elev= 30
  4526.9 1842.73  4532.5 1843.10  4538.6 1842.21  4553.5 1841.87  4562.0 1840.96
  4568.4 1841.55  4598.1 1839.95  4619.1 1840.29  4661.0 1838.40  4762.4 1836.09
  4977.4 1833.51  5013.2 1833.70  5038.2 1834.60  5043.5 1834.03  5105.1 1834.00
  5112.7 1833.28  5113.1 1832.78  5117.6 1832.78  5118.0 1833.28  5146.1 1834.04
  5171.4 1836.42  5197.4 1837.22  5289.8 1837.21  5341.1 1838.31  5352.4 1837.88
  5454.0 1839.92  5480.5 1841.33  5597.8 1844.18  5613.7 1845.19  5660.2 1844.82
#Mann=3,-1,0
  4526.9    0.05       0  5112.7    0.05       0  5118.0    0.05       0
Bank Sta=5112.7,5118
Exp/Cntr=0.3,0.1

Type RM Length L Ch R = 1,326,0,0,0
BEGIN DESCRIPTION:
Elm 01 83 955.217
END DESCRIPTION:
XS GIS Cut Line= 3
      1578487.66      6809121.76      1578805.38      6809599.21
      1579636.41      6809641.31
#Sta/Elev= 30
  4326.6 1838.50  4416.6 1837.46  4458.7 1836.13  4618.0 1835.16  4633.0 1834.16
  4711.2 1832.59  4855.5 1831.82  4870.5 1831.27  4876.5 1830.31  4909.7 1831.40
  4929.8 1830.71  4949.8 1831.37  5009.9 1831.05  5027.2 1829.35  5027.6 1828.85
  5032.5 1829.35  5039.9 1831.30  5080.0 1832.83  5130.0 1833.41  5150.0 1835.22
  5173.9 1835.00  5250.2 1836.49  5270.2 1837.89  5290.2 1837.54  5470.5 1839.32
  5540.5 1841.40  5560.6 1841.32  5566.8 1842.76  5630.7 1842.46  5732.2 1844.25
#Mann=3,-1,0
  4326.6    0.05       0  5027.2    0.05       0  5032.5    0.05       0
Bank Sta=5027.2,5032.5
Exp/Cntr=0.3,0.1

Chan Stop Cuts=-1