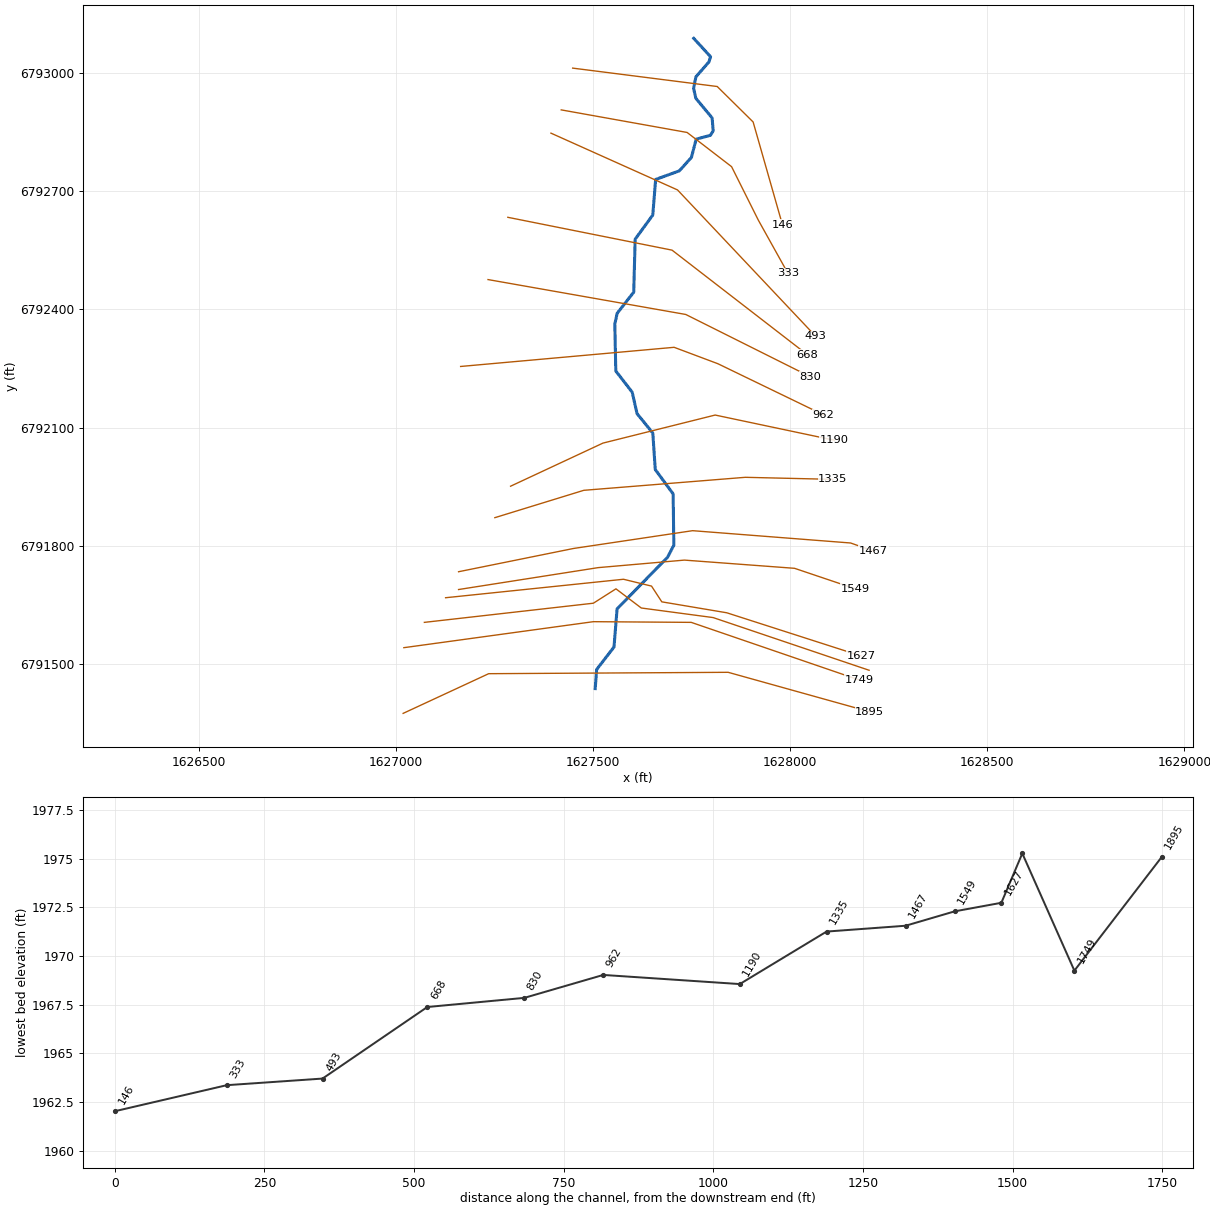
--- Elm 01 85.prj (project) ---

Proj Title=Elm 01 85 Base Level Engineering
Current Plan=p01
Default Exp/Contr=0.3,0.1
English Units
Geom File=g01
Flow File=f01
Plan File=p01
BEGIN DESCRIPTION:
Elm 01 85
END DESCRIPTION:

--- Elm 01 85.p01 (plan) ---

Plan Title=Multiple Run
Short Identifier=Multiple
Geom File=g01
Flow File=f01
Subcritical Flow
K Sum by GR= 0
Std Step Tol= 0.01
Critical Tol= 0.01
Num of Std Step Trials= 20
Max Error Tol= 0.3
Flow Tol Ratio= 0.001
Split Flow NTrial= 30
Split Flow Tol= 0.02
Split Flow Ratio= 0.02
Log Output Level= 0
Friction Slope Method= 1
Unsteady Friction Slope Method= 2
Unsteady Bridges Friction Slope Method= 1
Parabolic Critical Depth
Global Vel Dist=  1 , 1 , 1
Global Log Level= 0
CheckData=True
Encroach Param= -1, 0, 0, 0
BEGIN DESCRIPTION:
Multiple Run
END DESCRIPTION:

--- Elm 01 85.f01 (steady flow) ---

Flow Title=Multiple
Number of Profiles=7
Profile Names=10-year,25-year,50-year,1pct_min,100-year,1pct_plu,500-year
River Rch & RM= Elm 01 85,Reach-1,1895
     319     453     566     440     705     970    1110
Boundary for River Rch & Prof#=Elm 01 85,Reach-1,1
Up Type=0
Dn Type=3
Dn Slope=0.001
Boundary for River Rch & Prof#=Elm 01 85,Reach-1,2
Up Type=0
Dn Type=3
Dn Slope=0.001
Boundary for River Rch & Prof#=Elm 01 85,Reach-1,3
Up Type=0
Dn Type=3
Dn Slope=0.001
Boundary for River Rch & Prof#=Elm 01 85,Reach-1,4
Up Type=0
Dn Type=3
Dn Slope=0.001
Boundary for River Rch & Prof#=Elm 01 85,Reach-1,5
Up Type=0
Dn Type=3
Dn Slope=0.001
Boundary for River Rch & Prof#=Elm 01 85,Reach-1,6
Up Type=0
Dn Type=3
Dn Slope=0.001
Boundary for River Rch & Prof#=Elm 01 85,Reach-1,7
Up Type=0
Dn Type=3
Dn Slope=0.001

--- Elm 01 85.g01 (geometry) ---

Geom Title=Existing Conditions

River Reach=Elm 01 85,Reach-1
Reach XY= 30
      1627505.00      6791438.00      1627508.64      6791486.49
      1627552.66      6791543.51      1627560.52      6791640.43
      1627688.57      6791771.24      1627704.48      6791801.86
      1627702.75      6791932.06      1627657.36      6791993.98
      1627651.17      6792086.42      1627611.11      6792135.82
      1627598.88      6792190.18      1627557.23      6792243.93
      1627554.77      6792363.07      1627560.74      6792390.33
      1627602.73      6792443.94      1627606.39      6792578.34
      1627651.11      6792639.67      1627658.35      6792729.94
      1627718.28      6792751.66      1627749.14      6792785.79
      1627761.15      6792832.20      1627797.18      6792841.85
      1627804.29      6792852.99      1627801.71      6792885.93
      1627760.44      6792935.78      1627754.68      6792960.82
      1627760.49      6792990.31      1627793.56      6793028.17
      1627797.73      6793041.44      1627755.00      6793088.00

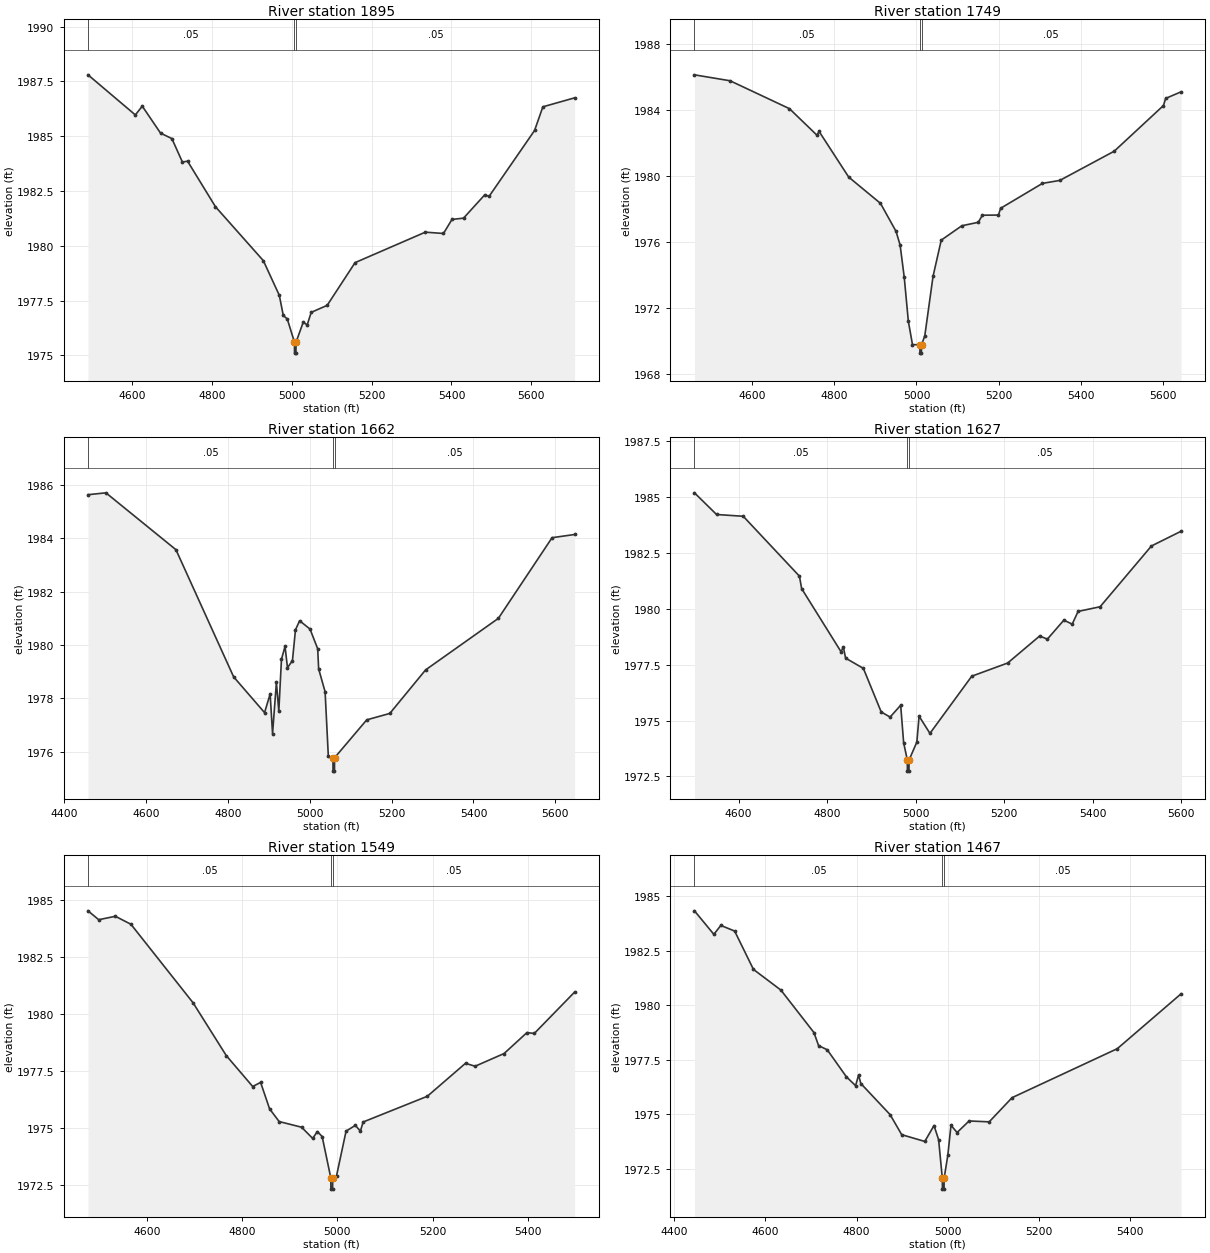
Type RM Length L Ch R = 1,1895,146,146,146
BEGIN DESCRIPTION:
Elm 01 85 2.0
END DESCRIPTION:
XS GIS Cut Line= 4
      1627017.67      6791375.19      1627234.72      6791475.90
      1627842.36      6791479.38      1628201.72      6791379.17
#Sta/Elev= 30
  4488.7 1987.80  4607.4 1985.97  4624.8 1986.37  4670.6 1985.14  4699.0 1984.89
  4725.4 1983.82  4738.3 1983.86  4808.3 1981.78  4928.3 1979.32  4968.3 1977.74
  4978.3 1976.82  4988.3 1976.66  5006.3 1975.60  5006.5 1975.10  5010.0 1975.10
  5010.3 1975.60  5028.3 1976.51  5038.3 1976.39  5048.3 1976.96  5088.3 1977.28
  5158.3 1979.23  5334.4 1980.62  5379.9 1980.56  5401.2 1981.20  5430.2 1981.26
  5483.7 1982.33  5494.1 1982.25  5608.3 1985.26  5629.1 1986.34  5708.7 1986.75
#Mann=3,-1,0
  4488.7    0.05       0  5006.3    0.03       0  5010.3    0.05       0
Bank Sta=5006.3,5010.3
Exp/Cntr=0.3,0.1

Type RM Length L Ch R = 1,1749,87,87,87
BEGIN DESCRIPTION:
Mapping XS 8aa491ee
END DESCRIPTION:
XS GIS Cut Line= 4
      1627019.43      6791541.88      1627500.34      6791607.85
      1627748.61      6791606.11      1628173.92      6791460.29
#Sta/Elev= 30
  4460.1 1986.12  4546.7 1985.76  4691.0 1984.07  4758.0 1982.46  4763.1 1982.69
  4835.2 1979.92  4912.4 1978.33  4950.3 1976.63  4960.2 1975.80  4970.2 1973.85
  4980.2 1971.18  4990.2 1969.77  5008.2 1969.75  5008.4 1969.25  5011.9 1969.25
  5012.2 1969.75  5020.2 1970.30  5040.2 1973.90  5060.2 1976.10  5110.2 1976.97
  5150.2 1977.18  5160.2 1977.61  5199.3 1977.62  5204.6 1978.03  5306.3 1979.54
  5348.5 1979.72  5480.8 1981.49  5600.6 1984.26  5605.9 1984.69  5643.4 1985.09
#Mann=3,-1,0
  4460.1    0.05       0  5008.2    0.05       0  5012.2    0.05       0
Bank Sta=5008.2,5012.2
Exp/Cntr=0.3,0.1

Type RM Length L Ch R = 1,1662,35,35,35
BEGIN DESCRIPTION:
Mapping XS 3675e62f
END DESCRIPTION:
XS GIS Cut Line= 6
      1627071.50      6791606.11      1627500.34      6791654.72
      1627557.64      6791691.18      1627621.87      6791642.57
      1627804.16      6791618.27      1628199.98      6791484.59
#Sta/Elev= 30
  4458.2 1985.63  4502.0 1985.70  4673.1 1983.57  4814.0 1978.81  4889.6 1977.47
  4903.2 1978.17  4909.1 1976.68  4918.5 1978.60  4924.4 1977.53  4930.9 1979.47
  4939.6 1979.95  4945.6 1979.15  4957.7 1979.42  4965.1 1980.57  4975.2 1980.91
  5000.6 1980.60  5019.4 1979.86  5021.7 1979.11  5037.5 1978.25  5045.4 1975.83
  5056.6 1975.78  5056.9 1975.28  5060.4 1975.28  5060.6 1975.78  5139.2 1977.20
  5195.6 1977.44  5283.0 1979.07  5460.8 1981.00  5592.0 1984.02  5647.1 1984.14
#Mann=3,-1,0
  4458.2    0.05       0  5056.6    0.05       0  5060.6    0.05       0
Bank Sta=5056.6,5060.6
Exp/Cntr=0.3,0.1

Type RM Length L Ch R = 1,1627,78,78,78
BEGIN DESCRIPTION:
Mapping XS 141cb81c
END DESCRIPTION:
XS GIS Cut Line= 6
      1627125.38      6791668.62      1627576.73      6791715.49
      1627647.91      6791698.13      1627673.96      6791658.20
      1627838.89      6791630.42      1628179.17      6791521.04
#Sta/Elev= 30
  4500.3 1985.20  4550.2 1984.23  4610.5 1984.15  4737.4 1981.47  4742.5 1980.91
  4831.6 1978.08  4836.6 1978.31  4841.7 1977.80  4881.9 1977.34  4922.2 1975.39
  4942.3 1975.16  4966.2 1975.69  4972.9 1974.01  4981.2 1973.24  4981.4 1972.74
  4984.9 1972.74  4985.2 1973.24  5002.7 1974.04  5007.8 1975.20  5032.3 1974.43
  5126.8 1976.99  5207.9 1977.58  5280.2 1978.79  5297.6 1978.65  5334.9 1979.50
  5353.7 1979.32  5367.0 1979.89  5416.8 1980.10  5532.7 1982.82  5599.7 1983.48
#Mann=3,-1,0
  4500.3    0.05       0  4981.2    0.05       0  4985.2    0.05       0
Bank Sta=4981.2,4985.2
Exp/Cntr=0.3,0.1

Type RM Length L Ch R = 1,1549,82,82,82
BEGIN DESCRIPTION:
Mapping XS cf6c8463
END DESCRIPTION:
XS GIS Cut Line= 5
      1627158.31      6791689.44      1627512.50      6791745.00
      1627731.25      6791764.10      1628010.76      6791743.27
      1628165.23      6791691.20
#Sta/Elev= 30
  4476.8 1984.53  4499.3 1984.14  4534.2 1984.29  4566.9 1983.94  4697.3 1980.49
  4767.0 1978.17  4822.5 1976.81  4839.1 1976.99  4857.9 1975.83  4878.0 1975.27
  4925.2 1975.02  4948.3 1974.53  4958.3 1974.83  4968.3 1974.61  4986.4 1972.80
  4986.7 1972.30  4990.2 1972.30  4990.4 1972.80  4998.4 1972.88  5018.5 1974.85
  5037.9 1975.10  5048.6 1974.85  5054.3 1975.25  5189.0 1976.38  5269.2 1977.83
  5289.3 1977.70  5350.2 1978.26  5398.2 1979.18  5413.5 1979.14  5498.2 1980.96
#Mann=3,-1,0
  4476.8    0.05       0  4986.4    0.05       0  4990.4    0.05       0
Bank Sta=4986.4,4990.4
Exp/Cntr=0.3,0.1

Type RM Length L Ch R = 1,1467,132,132,132
BEGIN DESCRIPTION:
Mapping XS 4fd9b014
END DESCRIPTION:
XS GIS Cut Line= 5
      1627158.31      6791734.58      1627450.00      6791793.61
      1627752.08      6791838.75      1628153.12      6791807.50
      1628211.03      6791787.06
#Sta/Elev= 30
  4444.8 1984.34  4487.3 1983.26  4502.6 1983.67  4532.9 1983.41  4574.1 1981.65
  4634.3 1980.70  4706.7 1978.75  4716.9 1978.15  4735.8 1977.96  4777.8 1976.72
  4798.0 1976.31  4804.5 1976.80  4809.5 1976.41  4873.7 1974.98  4899.1 1974.06
  4949.7 1973.75  4969.9 1974.48  4980.0 1973.83  4988.1 1972.06  4988.4 1971.56
  4991.9 1971.56  4992.1 1972.06  5000.2 1973.12  5007.1 1974.49  5020.5 1974.16
  5046.8 1974.69  5090.9 1974.65  5141.0 1975.76  5371.7 1978.01  5511.5 1980.53
#Mann=3,-1,0
  4444.8    0.05       0  4988.1    0.03       0  4992.1    0.05       0
Bank Sta=4988.1,4992.1
Exp/Cntr=0.3,0.1

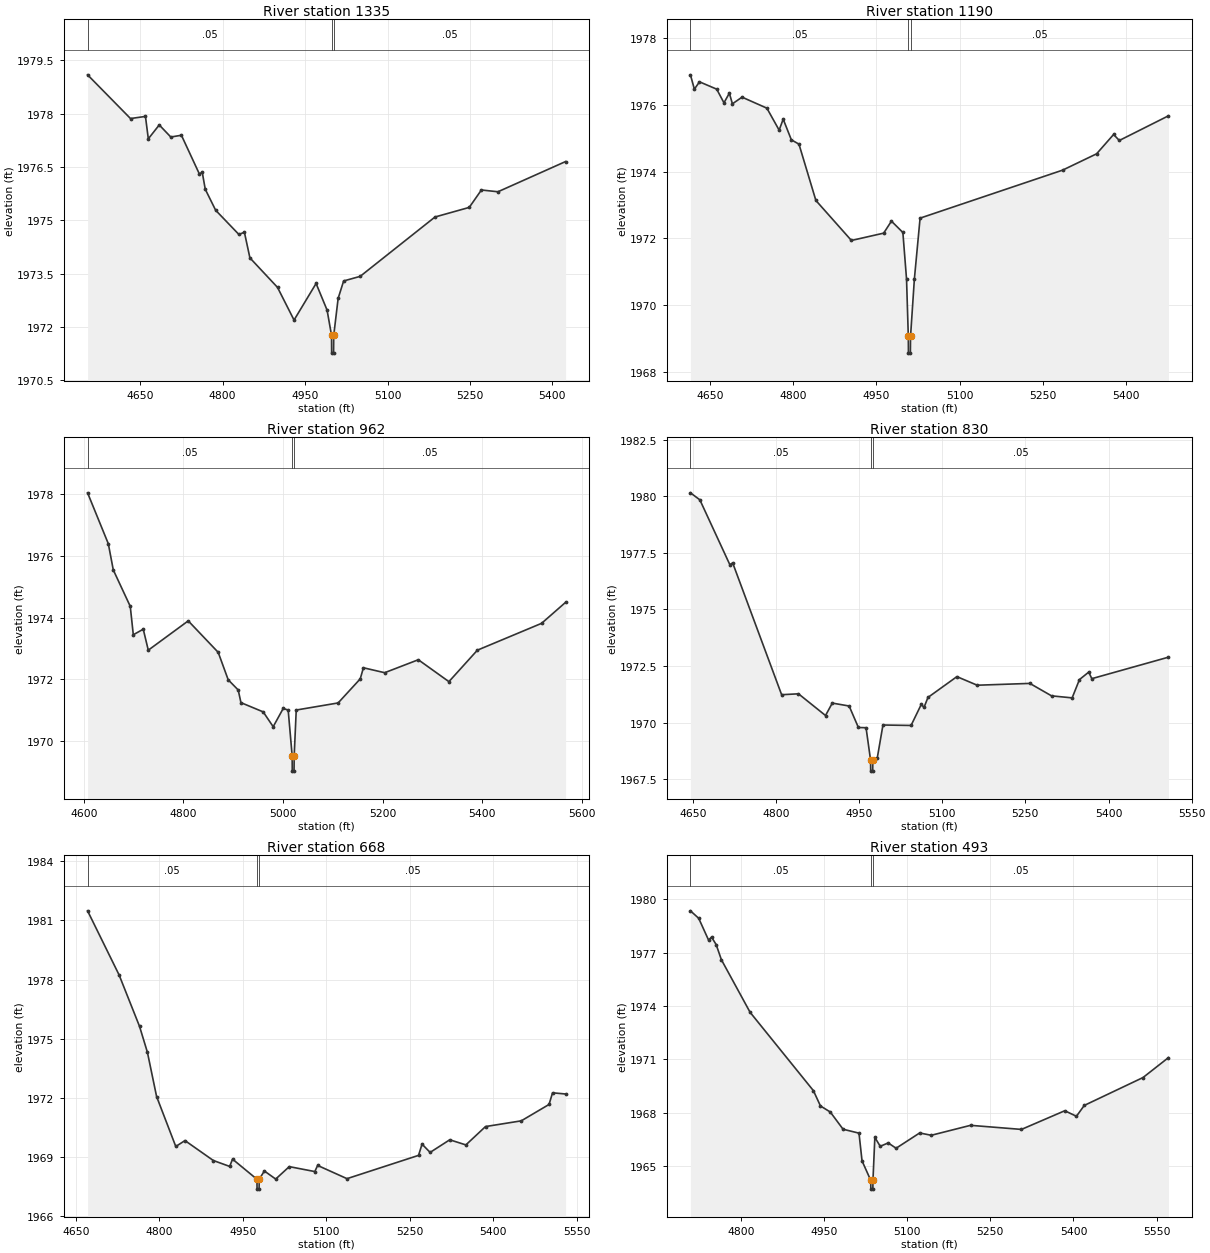
Type RM Length L Ch R = 1,1335,145,145,145
BEGIN DESCRIPTION:
Mapping XS 16d9c49f
END DESCRIPTION:
XS GIS Cut Line= 4
      1627250.34      6791871.74      1627476.04      6791941.18
      1627885.76      6791974.17      1628108.01      6791968.96
#Sta/Elev= 30
  4554.4 1979.09  4632.5 1977.86  4659.7 1977.92  4664.9 1977.29  4684.8 1977.68
  4705.8 1977.34  4725.1 1977.39  4757.8 1976.30  4763.0 1976.35  4768.5 1975.87
  4787.4 1975.28  4829.6 1974.60  4839.7 1974.66  4849.7 1973.94  4899.9 1973.11
  4930.0 1972.19  4970.1 1973.22  4990.1 1972.47  4998.2 1971.76  4998.4 1971.26
  5001.9 1971.26  5002.2 1971.76  5010.2 1972.80  5020.2 1973.29  5050.3 1973.42
  5186.4 1975.09  5248.7 1975.36  5270.8 1975.85  5300.9 1975.80  5423.9 1976.65
#Mann=3,-1,0
  4554.4    0.05       0  4998.2    0.05       0  5002.2    0.05       0
Bank Sta=4998.2,5002.2
Exp/Cntr=0.3,0.1

Type RM Length L Ch R = 1,1190,228,228,228
BEGIN DESCRIPTION:
Mapping XS 8616c913
END DESCRIPTION:
XS GIS Cut Line= 4
      1627290.24      6791951.58      1627524.65      6792060.97
      1627809.37      6792132.15      1628111.62      6792068.25
#Sta/Elev= 30
  4615.2 1976.91  4622.3 1976.48  4631.5 1976.70  4662.5 1976.48  4675.6 1976.07
  4685.3 1976.36  4690.8 1976.04  4708.2 1976.24  4752.9 1975.91  4775.0 1975.25
  4782.3 1975.58  4797.0 1974.96  4810.7 1974.83  4841.2 1973.14  4905.2 1971.94
  4963.3 1972.16  4977.3 1972.52  4997.9 1972.18  5004.5 1970.78  5007.7 1969.06
  5007.9 1968.56  5011.4 1968.56  5011.7 1969.06  5018.6 1970.78  5028.9 1972.61
  5285.6 1974.05  5346.9 1974.54  5377.5 1975.12  5387.8 1974.94  5476.3 1975.68
#Mann=3,-1,0
  4615.2    0.05       0  5007.7    0.05       0  5011.7    0.05       0
Bank Sta=5007.7,5011.7
Exp/Cntr=0.3,0.1

Type RM Length L Ch R = 1,962,132,132,132
BEGIN DESCRIPTION:
Mapping XS 7e00f238
END DESCRIPTION:
XS GIS Cut Line= 4
      1627163.52      6792255.42      1627705.21      6792304.03
      1627816.32      6792262.36      1628084.53      6792132.58
#Sta/Elev= 30
  4607.3 1978.05  4649.0 1976.40  4659.0 1975.55  4693.1 1974.37  4699.2 1973.45
  4719.2 1973.63  4729.3 1972.95  4809.6 1973.90  4869.8 1972.88  4889.9 1971.99
  4910.0 1971.66  4915.5 1971.25  4960.2 1970.95  4980.3 1970.47  5000.4 1971.06
  5010.4 1971.01  5018.4 1969.53  5018.6 1969.03  5022.2 1969.03  5022.5 1969.53
  5026.6 1971.01  5110.8 1971.24  5155.2 1972.02  5161.6 1972.38  5204.3 1972.22
  5271.9 1972.64  5333.4 1971.93  5390.6 1972.95  5519.6 1973.82  5567.8 1974.50
#Mann=3,-1,0
  4607.3    0.05       0  5018.4    0.05       0  5022.5    0.05       0
Bank Sta=5018.4,5022.5
Exp/Cntr=0.3,0.1

Type RM Length L Ch R = 1,830,162,162,162
BEGIN DESCRIPTION:
Mapping XS 021334b8
END DESCRIPTION:
XS GIS Cut Line= 3
      1627233.02      6792475.90      1627734.72      6792387.36
      1628050.32      6792229.56
#Sta/Elev= 30
  4645.8 1980.16  4662.8 1979.85  4716.9 1976.98  4722.0 1977.06  4810.3 1971.23
  4840.7 1971.27  4889.5 1970.31  4901.7 1970.86  4932.1 1970.73  4948.8 1969.78
  4962.6 1969.77  4970.7 1968.35  4971.0 1967.85  4974.6 1967.85  4974.8 1968.35
  4982.9 1968.44  4993.1 1969.89  5043.8 1969.87  5062.2 1970.80  5067.2 1970.67
  5074.3 1971.11  5126.5 1972.03  5163.1 1971.65  5258.1 1971.73  5297.2 1971.18
  5334.4 1971.09  5347.6 1971.90  5364.3 1972.23  5369.9 1971.94  5508.1 1972.89
#Mann=3,-1,0
  4645.8    0.05       0  4970.7    0.05       0  4974.8    0.05       0
Bank Sta=4970.7,4974.8
Exp/Cntr=0.3,0.1

Type RM Length L Ch R = 1,668,175,175,175
BEGIN DESCRIPTION:
Mapping XS 6487e65c
END DESCRIPTION:
XS GIS Cut Line= 3
      1627283.34      6792633.89      1627700.00      6792550.56
      1628043.72      6792284.95
#Sta/Elev= 30
  4670.8 1981.48  4727.5 1978.23  4764.3 1975.62  4778.4 1974.31  4794.9 1972.07
  4829.4 1969.54  4845.9 1969.84  4896.9 1968.83  4926.3 1968.53  4931.4 1968.90
  4975.3 1967.88  4975.5 1967.38  4979.1 1967.38  4979.4 1967.88  4988.6 1968.30
  5009.0 1967.89  5033.4 1968.52  5079.3 1968.27  5084.4 1968.58  5137.2 1967.91
  5265.8 1969.09  5272.1 1969.66  5286.6 1969.24  5321.9 1969.88  5350.9 1969.62
  5386.2 1970.55  5450.5 1970.84  5500.4 1971.67  5506.7 1972.26  5530.1 1972.20
#Mann=3,-1,0
  4670.8    0.05       0  4975.3    0.03       0  4979.4    0.05       0
Bank Sta=4975.3,4979.4
Exp/Cntr=0.3,0.1

Type RM Length L Ch R = 1,493,160,160,160
BEGIN DESCRIPTION:
Mapping XS 0cde6828
END DESCRIPTION:
XS GIS Cut Line= 3
      1627392.68      6792847.45      1627713.89      6792703.34
      1628063.99      6792332.43
#Sta/Elev= 30
  4709.2 1979.36  4724.1 1978.94  4741.8 1977.72  4747.3 1977.88  4755.6 1977.46
  4765.0 1976.61  4816.8 1973.65  4931.0 1969.24  4943.7 1968.38  4961.4 1968.04
  4984.5 1967.07  5013.2 1966.85  5018.7 1965.29  5034.3 1964.20  5034.6 1963.70
  5038.2 1963.70  5038.4 1964.20  5041.8 1966.61  5051.5 1966.11  5065.9 1966.30
  5080.1 1966.00  5122.6 1966.86  5143.6 1966.73  5214.4 1967.29  5306.2 1967.06
  5384.3 1968.11  5405.4 1967.80  5419.5 1968.41  5525.5 1969.98  5571.3 1971.10
#Mann=3,-1,0
  4709.2    0.05       0  5034.3    0.05       0  5038.4    0.05       0
Bank Sta=5034.3,5038.4
Exp/Cntr=0.3,0.1

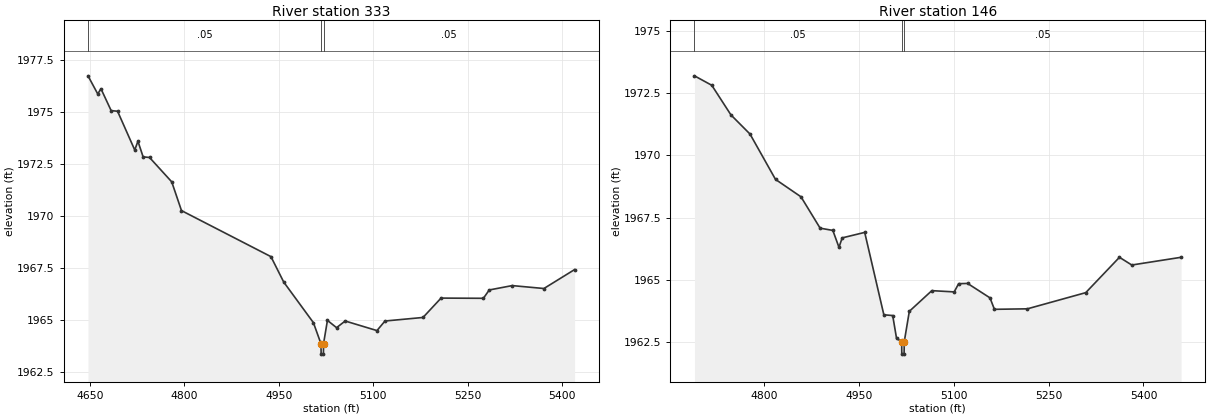
Type RM Length L Ch R = 1,333,187,187,187
BEGIN DESCRIPTION:
Mapping XS ffe8008d
END DESCRIPTION:
XS GIS Cut Line= 5
      1627418.76      6792906.46      1627738.19      6792849.17
      1627851.04      6792762.36      1627918.75      6792626.95
      1627994.27      6792491.36
#Sta/Elev= 30
  4646.7 1976.72  4662.2 1975.85  4667.3 1976.10  4683.5 1975.05  4693.7 1975.02
  4721.0 1973.16  4726.1 1973.58  4734.3 1972.83  4744.5 1972.80  4779.8 1971.63
  4795.3 1970.25  4937.5 1968.04  4957.8 1966.82  5005.0 1964.87  5017.0 1963.86
  5017.3 1963.36  5020.9 1963.36  5021.1 1963.86  5027.3 1964.98  5041.8 1964.63
  5055.5 1964.95  5106.0 1964.49  5118.8 1964.95  5179.2 1965.12  5207.9 1966.05
  5275.2 1966.04  5284.5 1966.44  5321.0 1966.65  5371.4 1966.51  5420.2 1967.42
#Mann=3,-1,0
  4646.7    0.05       0  5017.0    0.03       0  5021.1    0.05       0
Bank Sta=5017,5021.1
Exp/Cntr=0.3,0.1

Type RM Length L Ch R = 1,146,0,0,0
BEGIN DESCRIPTION:
Elm 01 85 1.0
END DESCRIPTION:
XS GIS Cut Line= 4
      1627447.81      6793012.44      1627814.58      6792965.78
      1627905.73      6792875.72      1627980.29      6792614.20
#Sta/Elev= 30
  4689.7 1973.20  4717.1 1972.82  4747.4 1971.63  4777.6 1970.86  4817.9 1969.04
  4858.2 1968.34  4888.5 1967.08  4908.6 1966.99  4918.3 1966.31  4923.4 1966.69
  4959.0 1966.91  4989.3 1963.60  5003.3 1963.57  5009.4 1962.65  5017.5 1962.52
  5017.7 1962.02  5021.3 1962.02  5021.6 1962.52  5029.6 1963.74  5065.2 1964.57
  5100.6 1964.52  5107.6 1964.85  5121.8 1964.86  5157.2 1964.28  5164.2 1963.82
  5216.4 1963.84  5308.7 1964.49  5362.0 1965.91  5381.5 1965.60  5459.5 1965.91
#Mann=3,-1,0
  4689.7    0.05       0  5017.5    0.05       0  5021.6    0.05       0
Bank Sta=5017.5,5021.6
Exp/Cntr=0.3,0.1

Chan Stop Cuts=-1