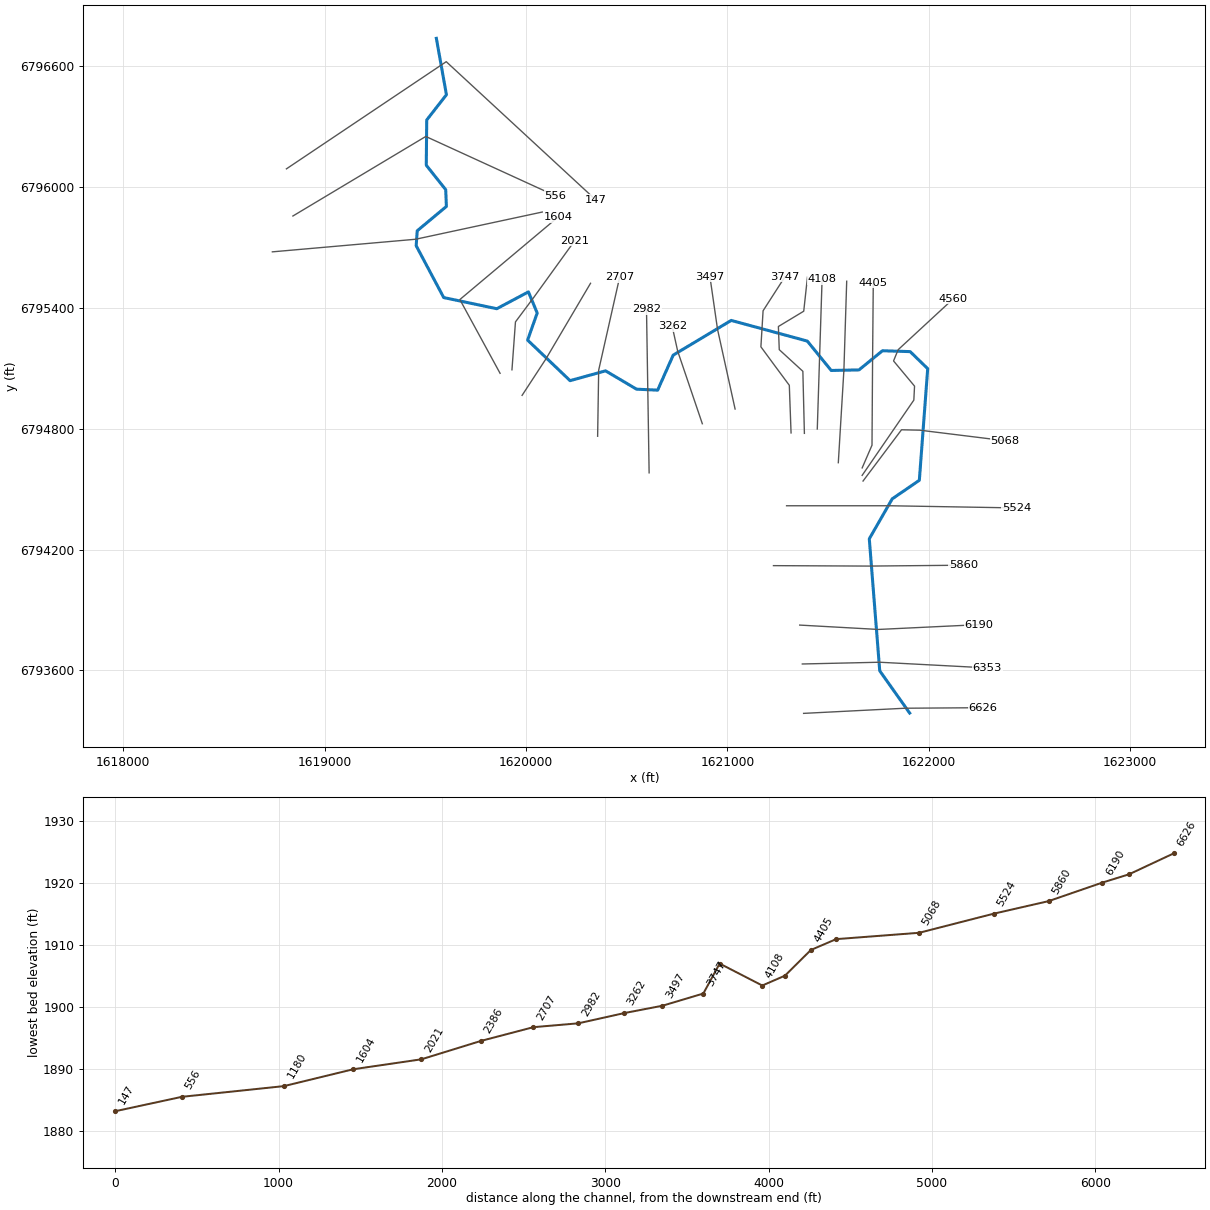
--- Elm 01 86.prj (project) ---

Proj Title=Elm 01 86 Base Level Engineering
Current Plan=p01
Default Exp/Contr=0.3,0.1
English Units
Geom File=g01
Flow File=f01
Plan File=p01
Y Axis Title=Elevation
X Axis Title(PF)=Main Channel Distance
X Axis Title(XS)=Station
BEGIN DESCRIPTION:
Elm 01 86
END DESCRIPTION:
DSS Export Rating Curves= 0
DSS Export Rating Curve Sorted= 0
DSS Export Volume Flow Curves= 0
DXF OffsetX= 0
DXF OffsetY= 0
DXF ScaleX= 1
DXF ScaleY= 10

--- Elm 01 86.p01 (plan) ---

Plan Title=Multiple Run
Short Identifier=Multiple
Geom File=g01
Flow File=f01
Subcritical Flow
K Sum by GR= 0
Std Step Tol= 0.01
Critical Tol= 0.01
Num of Std Step Trials= 20
Max Error Tol= 0.3
Flow Tol Ratio= 0.001
Split Flow NTrial= 30
Split Flow Tol= 0.02
Split Flow Ratio= 0.02
Log Output Level= 0
Friction Slope Method= 1
Unsteady Friction Slope Method= 2
Unsteady Bridges Friction Slope Method= 1
Parabolic Critical Depth
Global Vel Dist=  1 , 1 , 1
Global Log Level= 0
CheckData=True
Encroach Param= -1, 0, 0, 0
BEGIN DESCRIPTION:
Multiple Run
END DESCRIPTION:

--- Elm 01 86.f01 (steady flow) ---

Flow Title=Multiple
Number of Profiles=7
Profile Names=10-year,25-year,50-year,1pct_min,100-year,1pct_plu,500-year
River Rch & RM= Elm 01 86,Reach-1,6626
     378     548     695     548     878    1210    1420
River Rch & RM= Elm 01 86,Reach-1,5068
     467     683     872     691    1110    1520    1810
River Rch & RM= Elm 01 86,Reach-1,1180
     709    1070    1380    1110    1790    2460    3020
Boundary for River Rch & Prof#=Elm 01 86,Reach-1,1
Up Type=0
Dn Type=3
Dn Slope=0.001
Boundary for River Rch & Prof#=Elm 01 86,Reach-1,2
Up Type=0
Dn Type=3
Dn Slope=0.001
Boundary for River Rch & Prof#=Elm 01 86,Reach-1,3
Up Type=0
Dn Type=3
Dn Slope=0.001
Boundary for River Rch & Prof#=Elm 01 86,Reach-1,4
Up Type=0
Dn Type=3
Dn Slope=0.001
Boundary for River Rch & Prof#=Elm 01 86,Reach-1,5
Up Type=0
Dn Type=3
Dn Slope=0.001
Boundary for River Rch & Prof#=Elm 01 86,Reach-1,6
Up Type=0
Dn Type=3
Dn Slope=0.001
Boundary for River Rch & Prof#=Elm 01 86,Reach-1,7
Up Type=0
Dn Type=3
Dn Slope=0.001

--- Elm 01 86.g01 (geometry) ---

Geom Title=Existing Conditions
Program Version=4.10

River Reach=Elm 01 86       ,Reach-1
Reach XY= 30
        1621905.        6793388.      1621756.36      6793597.65
      1621704.51       6794253.2      1621818.49      6794451.56
      1621953.02      6794543.67      1621994.53      6795097.83
      1621907.46      6795182.55      1621769.82      6795186.86
      1621653.47      6795091.73      1621515.43      6795089.03
      1621396.69      6795234.92      1621018.97      6795337.47
      1620731.05      6795165.19      1620653.75      6794991.36
      1620548.95      6794996.04      1620395.16      6795087.09
      1620218.91       6795038.4      1620008.13      6795239.63
      1620055.74      6795374.34      1620012.07      6795479.03
      1619855.01      6795395.53       1619591.5      6795450.92
      1619454.83      6795708.26      1619460.11      6795782.53
      1619604.77      6795903.21      1619601.53       6795986.5
      1619504.96      6796107.98      1619507.18      6796332.55
      1619605.04      6796457.99        1619555.        6796738.

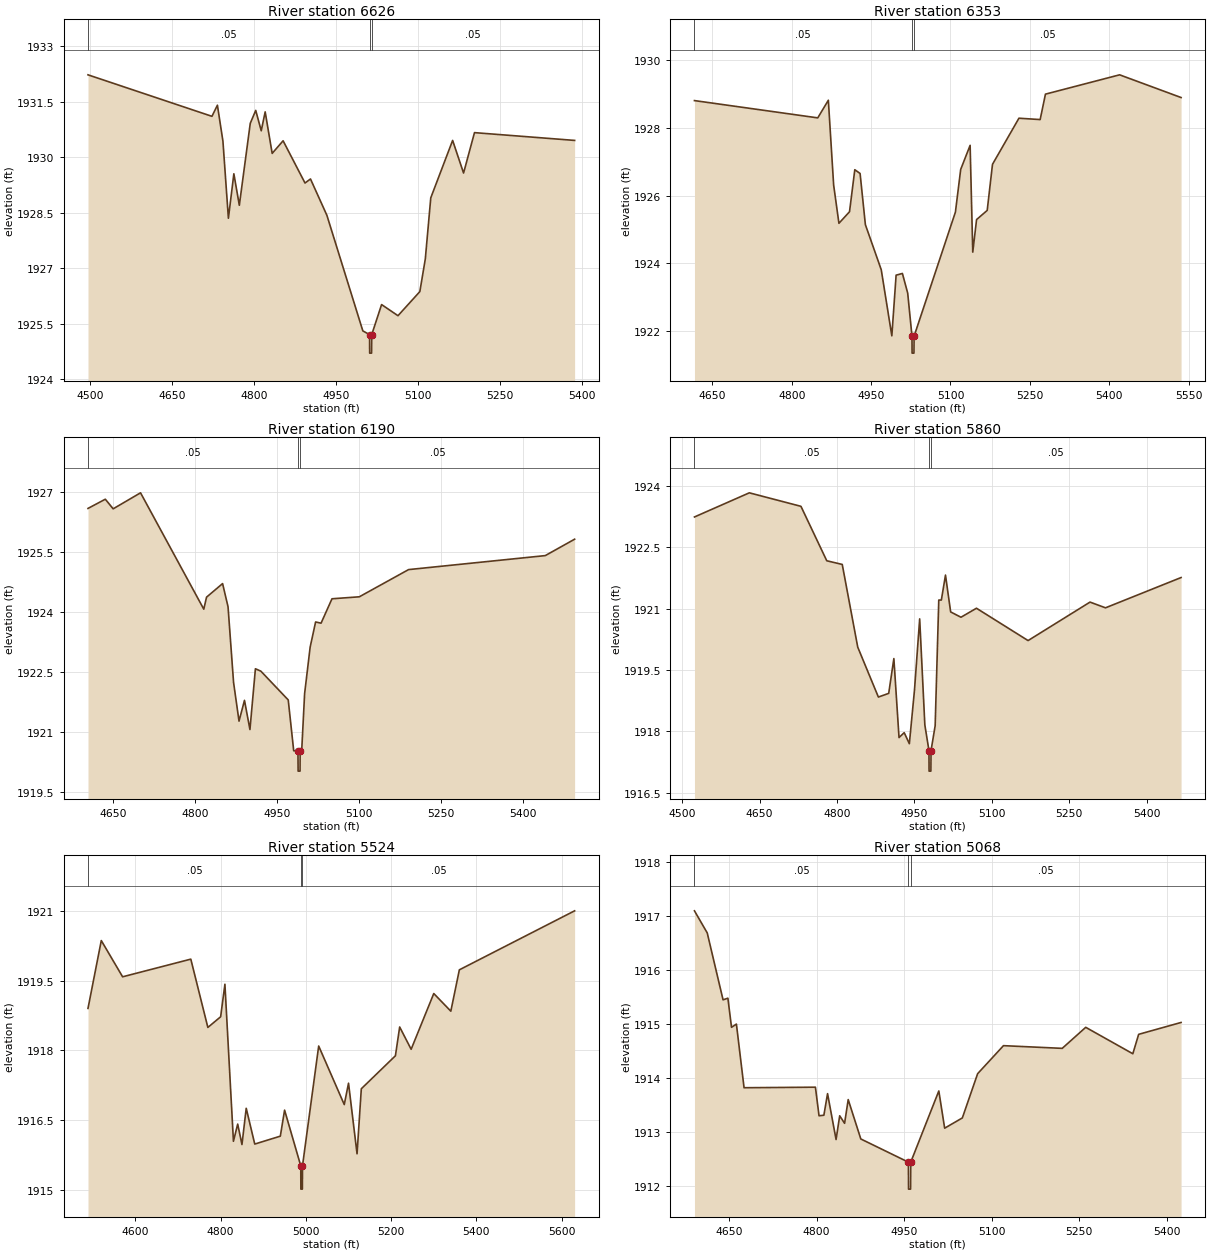
Type RM Length L Ch R = 1 ,6626    ,273,273,273
BEGIN DESCRIPTION:
Elm 01 86 6166.012
END DESCRIPTION:
XS GIS Cut Line= 3
      1621378.46      6793386.43      1621881.51        6793412.
       1622268.2      6793414.64
#Sta/Elev= 30
  4496.3 1932.22  4723.1  1931.1  4733.1  1931.4  4743.2 1930.43  4753.2 1928.35
  4763.2 1929.55  4773.2  1928.7  4793.2 1930.91  4803.2 1931.26  4813.3 1930.71
  4820.5 1931.22  4833.3  1930.1  4853.3 1930.44  4893.4  1929.3  4903.4 1929.41
  4933.4 1928.43  4999.2 1925.31  5011.5 1925.21  5011.7 1924.71  5015.2 1924.71
  5015.5 1925.21  5033.5 1926.02  5063.5 1925.72  5103.5 1926.37  5113.5 1927.25
  5123.5  1928.9  5163.5 1930.45  5183.5 1929.57  5203.5 1930.66  5386.7 1930.45
#Mann= 3 ,-1 , 0
  4496.3     .05       0  5011.5     .05       0  5015.5     .05       0
Bank Sta=5011.5,5015.5
XS Rating Curve= 0 ,0
Exp/Cntr=0.3,0.1

Type RM Length L Ch R = 1 ,6353    ,163,163,163
BEGIN DESCRIPTION:
Elm 01 86 6353.18
END DESCRIPTION:
XS GIS Cut Line= 3
      1621371.98      6793631.66      1621756.07      6793640.34
      1622291.04      6793612.18
#Sta/Elev= 30
    4616  1928.8  4849.1 1928.29  4869.1 1928.81  4879.1 1926.31  4889.1 1925.18
  4909.1 1925.52  4919.1 1926.76  4929.1 1926.65  4939.1 1925.14  4969.1 1923.81
  4989.1 1921.86  4997.2 1923.65  5009.1  1923.7  5019.1 1923.12  5027.2 1921.85
  5027.4 1921.35  5030.9 1921.35  5031.2 1921.85  5109.3 1925.51  5119.3 1926.77
  5137.1 1927.48  5142.1 1924.33  5149.3 1925.29  5169.4 1925.56  5179.4 1926.92
  5229.4 1928.28  5269.5 1928.24  5279.5 1928.99  5419.7 1929.56  5535.9 1928.89
#Mann= 3 ,-1 , 0
    4616     .05       0  5027.2     .05       0  5031.2     .05       0
Bank Sta=5027.2,5031.2
XS Rating Curve= 0 ,0
Exp/Cntr=0.3,0.1

Type RM Length L Ch R = 1 ,6190    ,330,330,330
BEGIN DESCRIPTION:
Elm 01 86 6190.19
END DESCRIPTION:
XS GIS Cut Line= 3
      1621358.96       6793824.8      1621749.56       6793803.1
      1622248.69      6793826.97
#Sta/Elev= 30
  4604.3 1926.59    4636 1926.82  4650.4 1926.58  4700.5 1926.98  4816.3 1924.07
  4821.3 1924.37  4850.7 1924.71  4860.7 1924.13  4870.8 1922.24  4880.8 1921.27
  4890.8 1921.79  4900.8 1921.06  4910.8 1922.58  4920.8 1922.52  4970.9  1921.8
  4980.9 1920.53  4988.7 1920.52    4989 1920.02  4992.5 1920.02  4992.7 1920.52
  4995.5 1920.52  5000.9 1921.96    5011 1923.12    5021 1923.75    5031 1923.72
    5051 1924.33  5101.1 1924.38  5191.2 1925.06  5441.5 1925.41  5495.2 1925.82
#Mann= 3 ,-1 , 0
  4604.3     .05       0  4988.7     .03       0  4992.7     .05       0
Bank Sta=4988.7,4992.7
XS Rating Curve= 0 ,0
Exp/Cntr=0.3,0.1

Type RM Length L Ch R = 1 ,5860    ,336,336,336
BEGIN DESCRIPTION:
Elm 01 86 5860.15
END DESCRIPTION:
XS GIS Cut Line= 3
      1621228.74      6794119.94      1621703.99      6794117.77
      1622171.41       6794122.1
#Sta/Elev= 30
    4524 1923.24  4630.3 1923.83  4730.3  1923.5  4780.3 1922.17  4810.3 1922.08
  4840.3 1920.06  4880.3 1918.84  4900.3 1918.93  4910.3 1919.78  4920.3 1917.85
  4930.3 1917.97  4940.3  1917.7  4950.3 1919.02  4960.3 1920.75  4970.3 1918.16
  4978.3 1917.53  4978.5 1917.03    4982 1917.03  4982.3 1917.53  4990.3 1918.14
  4997.3 1921.21  5002.3 1921.21  5010.3 1921.82  5020.3 1920.92  5040.3 1920.79
  5070.3 1921.01  5170.3 1920.22  5290.3 1921.16  5320.3 1921.02  5466.7 1921.76
#Mann= 3 ,-1 , 0
    4524     .05       0  4978.3     .05       0  4982.3     .05       0
Bank Sta=4978.3,4982.3
XS Rating Curve= 0 ,0
Exp/Cntr=0.3,0.1

Type RM Length L Ch R = 1 ,5524    ,456,456,456
BEGIN DESCRIPTION:
Elm 01 86 5524.42
END DESCRIPTION:
XS GIS Cut Line= 3
      1621293.81      6794417.25      1621808.15      6794417.25
      1622435.31       6794406.4
#Sta/Elev= 30
    4489  1918.9  4520.2 1920.36  4570.2 1919.58  4730.2 1919.96  4770.2 1918.49
  4800.2 1918.72  4810.2 1919.42  4830.2 1916.04  4840.2 1916.41  4850.2 1915.97
  4860.2 1916.75  4880.2 1915.98  4940.2 1916.15  4950.2 1916.71  4988.2 1915.51
  4988.4 1915.01  4991.9 1915.01  4992.2 1915.51  5030.2 1918.09  5090.2 1916.83
  5100.2 1917.29  5120.2 1915.77  5130.2 1917.17  5210.2 1917.88  5220.2  1918.5
  5247.1 1918.02  5300.2 1919.22  5340.2 1918.84  5360.2 1919.73  5630.6    1921
#Mann= 3 ,-1 , 0
    4489     .05       0  4988.2     .05       0  4992.2     .05       0
Bank Sta=4988.2,4992.2
XS Rating Curve= 0 ,0
Exp/Cntr=0.3,0.1

Type RM Length L Ch R = 1 ,5068    ,508,508,508
BEGIN DESCRIPTION:
Elm 01 86 5067.54
END DESCRIPTION:
XS GIS Cut Line= 4
      1621673.49        6794540.      1621864.52      6794794.45
      1621955.22       6794792.5      1622377.12      6794740.41
#Sta/Elev= 30
  4590.8  1917.1  4612.7 1916.69  4639.8 1915.45  4648.1 1915.48  4654.3 1914.94
  4662.7    1915  4675.8 1913.82  4798.1 1913.83  4804.3  1913.3  4812.6 1913.31
  4818.9 1913.71  4833.5 1912.86  4839.7  1913.3  4848.1 1913.16  4854.3  1913.6
  4875.9 1912.87  4957.5 1912.44  4957.7 1911.94  4961.2 1911.94  4961.5 1912.44
  5009.6 1913.76  5019.6 1913.07  5049.9 1913.26  5076.1 1914.08  5120.4  1914.6
  5221.1 1914.55  5261.4 1914.94  5342.1 1914.45  5352.1 1914.81  5424.8 1915.03
#Mann= 3 ,-1 , 0
  4590.8     .05       0  4957.5     .03       0  4961.5     .05       0
Bank Sta=4957.5,4961.5
XS Rating Curve= 0 ,0
Exp/Cntr=0.3,0.1

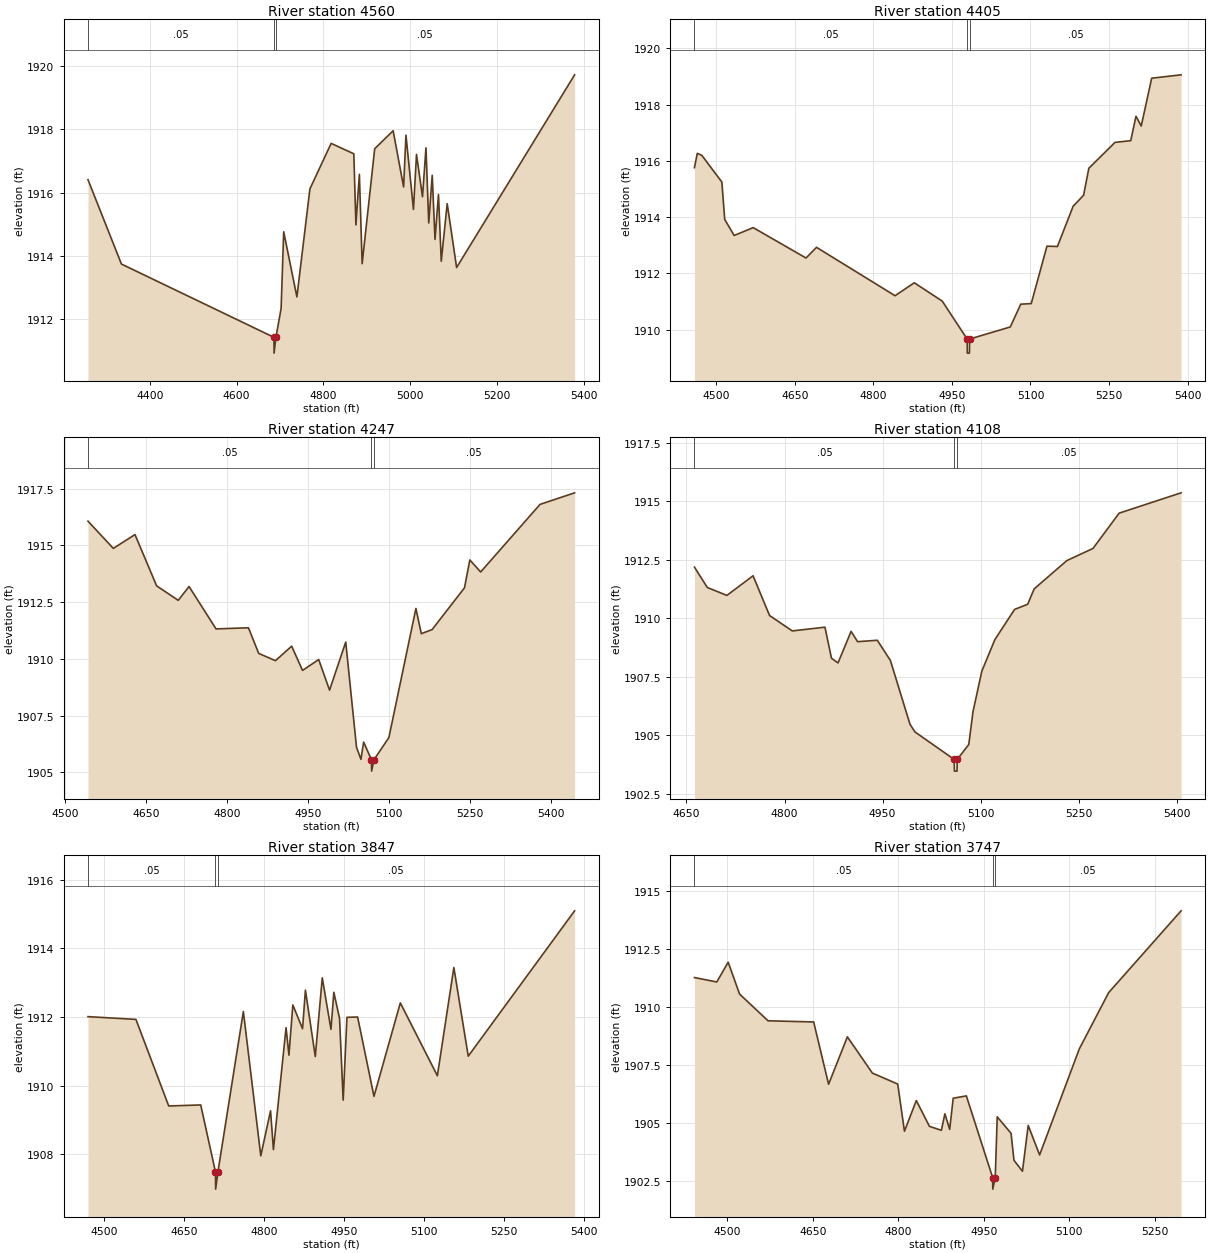
Type RM Length L Ch R = 1 ,4560    ,155,155,155
BEGIN DESCRIPTION:
Elm 01 86 4560.22
END DESCRIPTION:
XS GIS Cut Line= 6
      1621669.13      6794568.18       1621925.7      6794941.81
      1621929.18      6795011.25      1621825.01      6795136.25
      1621847.58      6795191.81      1622121.87      6795445.26
#Sta/Elev= 30
  4257.6 1916.41  4334.6 1913.74  4685.9 1911.42  4686.2 1910.92  4690.5 1911.42
  4702.4 1912.33  4708.4 1914.76  4738.8  1912.7  4768.8 1916.12  4817.7 1917.56
  4869.9 1917.23  4874.7 1914.98  4882.7 1916.58  4889.1 1913.75    4918 1917.39
  4960.5 1917.96  4984.6 1916.18    4990 1917.82  5007.3 1915.47  5014.3 1917.21
  5028.1 1915.87  5036.1 1917.42  5042.5 1915.04  5050.5 1916.55  5056.9 1914.52
  5064.9 1915.94  5071.3 1913.83    5085 1915.65  5106.7 1913.63  5378.5 1919.73
#Mann= 3 ,-1 , 0
  4257.6     .05       0  4685.9     .05       0  4690.5     .05       0
Bank Sta=4685.9,4690.5
XS Rating Curve= 0 ,0
Exp/Cntr=0.3,0.1

Type RM Length L Ch R = 1 ,4405    ,158,158,158
BEGIN DESCRIPTION:
Elm 01 86 4404.73
END DESCRIPTION:
XS GIS Cut Line= 4
      1621669.15      6794605.11      1621717.99      6794717.97
      1621720.84      6795141.46      1621724.31      6795524.07
#Sta/Elev= 30
  4458.5 1915.76  4463.9 1916.27  4472.5  1916.2  4510.8 1915.25  4516.3 1913.92
  4534.3 1913.35  4570.6 1913.63  4671.5 1912.55  4691.5 1912.93  4841.5 1911.21
  4878.2 1911.67  4931.5 1911.02  4979.2 1909.67  4979.5 1909.17  4983.5 1909.17
  4983.8 1909.67  5061.5  1910.1  5081.5 1910.91  5101.5 1910.93  5131.5 1912.97
  5151.5 1912.96  5181.5 1914.39  5201.5 1914.78  5211.5 1915.74  5261.5 1916.66
  5291.5 1916.72  5301.5 1917.59  5311.5 1917.24  5331.5 1918.94  5387.6 1919.06
#Mann= 3 ,-1 , 0
  4458.5     .05       0  4979.2     .03       0  4983.8     .05       0
Bank Sta=4979.2,4983.8
XS Rating Curve= 0 ,0
Exp/Cntr=0.3,0.1

Type RM Length L Ch R = 1 ,4247    ,139,139,139
BEGIN DESCRIPTION:
Elm 01 86 4247.17
END DESCRIPTION:
XS GIS Cut Line= 3
       1621550.7      6794631.04      1621578.48      6795091.11
      1621592.37      6795532.09
#Sta/Elev= 30
    4542 1916.07    4589 1914.87  4629.1 1915.48  4669.2 1913.22  4709.3 1912.58
  4729.3 1913.19  4779.4 1911.32  4839.5 1911.37  4858.4 1910.24  4889.6 1909.92
  4919.6 1910.56  4939.7 1909.49  4969.7 1909.97  4989.8 1908.62  5019.8 1910.74
  5039.8  1906.1    5048 1905.57    5053 1906.33  5067.5 1905.55  5067.8 1905.05
  5072.1 1905.55  5099.8 1906.53  5149.9 1912.22  5159.9 1911.11  5179.9 1911.29
  5239.9 1913.13  5249.9 1914.36  5269.9 1913.83    5380 1916.81  5444.1 1917.32
#Mann= 3 ,-1 , 0
    4542     .05       0  5067.5     .03       0  5072.1     .05       0
Bank Sta=5067.5,5072.1
XS Rating Curve= 0 ,0
Exp/Cntr=0.3,0.1

Type RM Length L Ch R = 1 ,4108    ,261,261,261
BEGIN DESCRIPTION:
Elm 01 86 4108.28
END DESCRIPTION:
XS GIS Cut Line= 3
      1621446.32      6794798.39      1621457.17      6795137.99
      1621470.19      6795542.71
#Sta/Elev= 30
  4662.2 1912.19  4681.8 1911.32  4711.8 1910.98  4751.9 1911.82  4777.1 1910.12
  4811.9 1909.46  4861.9 1909.62  4871.9 1908.29  4881.9 1908.09  4901.9 1909.44
  4911.9    1909    4942 1909.06    4962  1908.2    4992 1905.47  4999.5 1905.14
  5059.7 1903.96    5060 1903.46    5064 1903.46  5064.3 1903.96    5082  1904.6
  5088.5 1906.01    5102 1907.74    5122 1909.09  5152.1 1910.38  5172.1  1910.6
  5182.1 1911.26  5232.1 1912.47  5272.1 1912.99  5312.1  1914.5  5406.9 1915.37
#Mann= 3 ,-1 , 0
  4662.2     .05       0  5059.7     .05       0  5064.3     .05       0
Bank Sta=5059.7,5064.3
XS Rating Curve= 0 ,0
Exp/Cntr=0.3,0.1

Type RM Length L Ch R = 1 ,3847    ,100,100,100
BEGIN DESCRIPTION:
Elm 01 86 3846.95
END DESCRIPTION:
XS GIS Cut Line= 6
       1621382.3      6794776.68      1621374.71      6795084.82
      1621257.52      6795192.24      1621253.18      6795307.26
      1621379.05      6795383.21      1621397.49      6795552.49
#Sta/Elev= 30
  4469.6 1912.01  4559.5 1911.93    4621 1909.41    4681 1909.44  4708.7 1907.49
    4709 1906.99  4713.3 1907.49    4761 1912.16  4793.7 1907.96    4812 1909.27
  4817.4 1908.14  4841.1 1911.69  4846.5 1910.89  4853.8 1912.35    4872 1911.66
  4877.4 1912.78  4895.9 1910.85    4909 1913.14  4925.3 1911.64  4930.7 1912.72
  4941.4 1911.96  4948.2 1909.58  4955.3 1911.99  4975.3    1912    5006 1909.69
  5055.4 1912.41  5124.9 1910.29  5155.8 1913.44  5182.8 1910.86  5382.3 1915.09
#Mann= 3 ,-1 , 0
  4469.6     .05       0  4708.7     .05       0  4713.3     .05       0
Bank Sta=4708.7,4713.3
XS Rating Curve= 0 ,0
Exp/Cntr=0.3,0.1

Type RM Length L Ch R = 1 ,3747    ,250,250,250
BEGIN DESCRIPTION:
Elm 01 86 3747.29
END DESCRIPTION:
XS GIS Cut Line= 6
      1621316.11      6794778.86      1621307.43      6795015.37
      1621235.82      6795111.94      1621166.37      6795206.35
      1621177.22      6795385.38      1621285.94      6795554.38
#Sta/Elev= 30
  4442.2 1911.27  4481.4 1911.08  4501.4 1911.93  4521.4 1910.56  4571.4 1909.41
  4651.5 1909.36  4677.7 1906.68  4710.7 1908.72  4754.6 1907.16  4799.1 1906.69
  4810.9 1904.66  4831.7 1905.98  4854.8 1904.87  4875.7  1904.7  4881.9 1905.41
  4890.3 1904.74  4896.5 1906.08  4919.6 1906.18  4965.7 1902.67    4966 1902.17
  4970.3 1902.67  4973.8 1905.28  4998.1 1904.57  5003.2 1903.41  5018.1 1902.94
  5028.2 1904.91  5048.2 1903.64  5117.9  1908.2  5169.4 1910.62  5296.6 1914.14
#Mann= 3 ,-1 , 0
  4442.2     .05       0  4965.7     .05       0  4970.3     .05       0
Bank Sta=4965.7,4970.3
XS Rating Curve= 0 ,0
Exp/Cntr=0.3,0.1

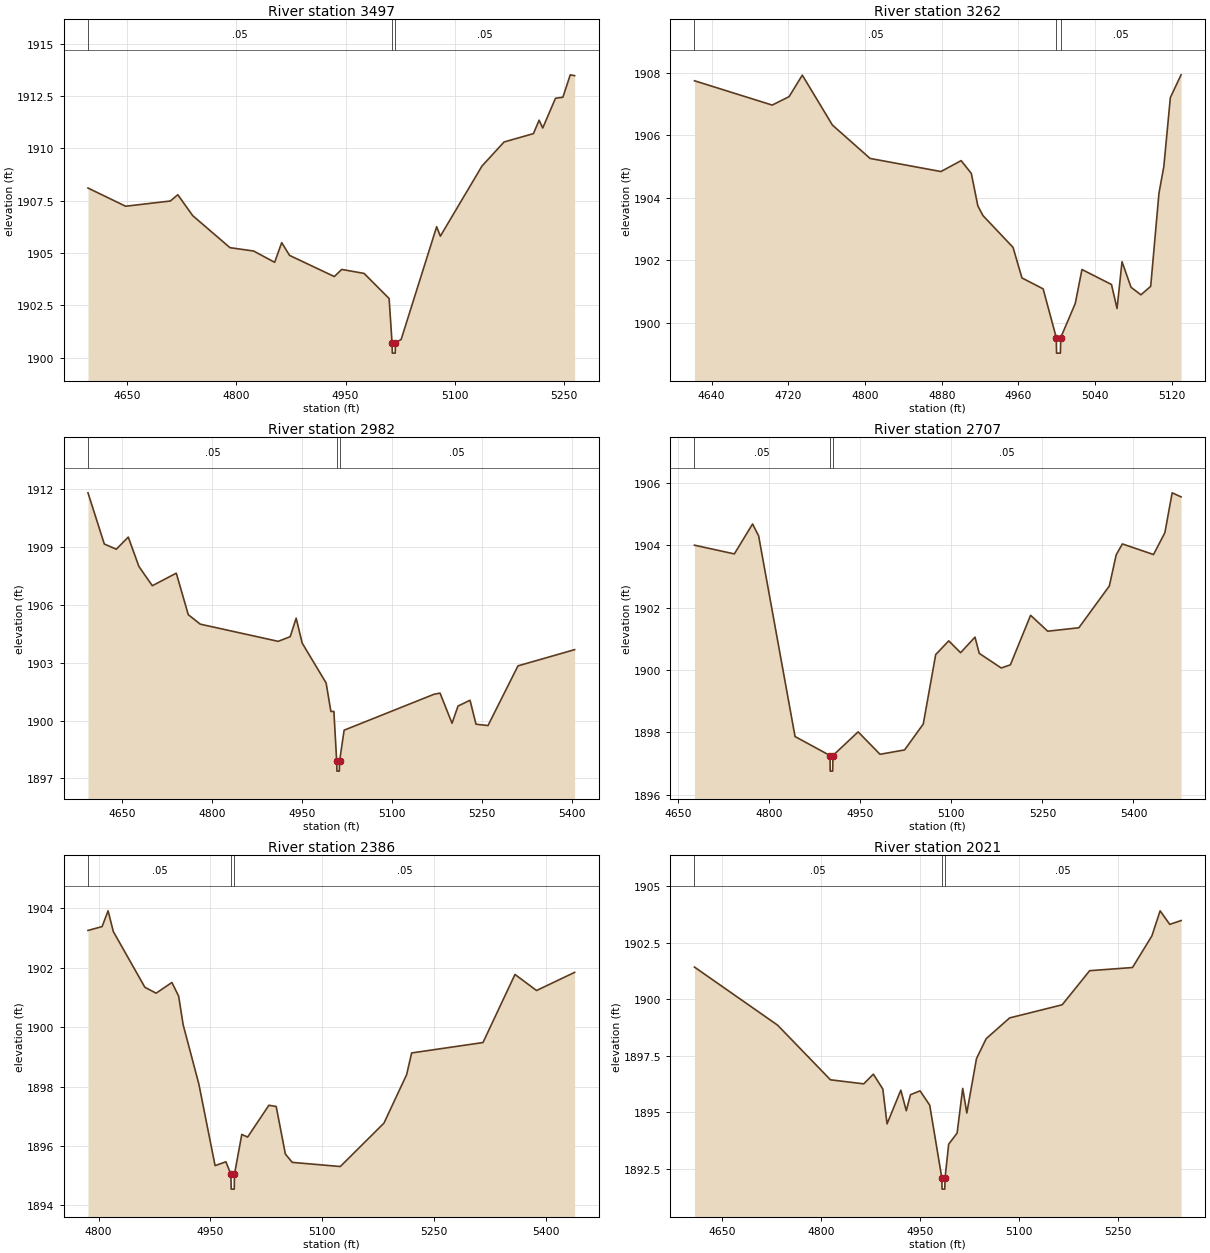
Type RM Length L Ch R = 1 ,3497    ,235,235,235
BEGIN DESCRIPTION:
Elm 01 86 3496.97
END DESCRIPTION:
XS GIS Cut Line= 3
      1621038.26      6794897.48      1620951.02       6795293.3
      1620913.41      6795553.98
#Sta/Elev= 30
  4596.1  1908.1  4647.8 1907.23  4709.3 1907.48  4719.5 1907.78    4740 1906.78
  4791.2 1905.25  4823.7 1905.09  4852.6 1904.55  4862.3 1905.49  4873.1 1904.88
  4934.6 1903.87  4944.8 1904.21  4975.5 1904.02  5009.9 1902.82  5013.9 1900.71
  5014.3 1900.21  5018.3 1900.21  5018.6 1900.71  5026.4 1900.86  5075.2 1906.25
  5080.3  1905.8  5137.5 1909.15  5167.8  1910.3  5208.2  1910.7    5216 1911.34
    5221 1910.97  5238.5 1912.39  5248.7 1912.44  5258.8 1913.51  5264.8 1913.47
#Mann= 3 ,-1 , 0
  4596.1     .05       0  5013.9     .05       0  5018.6     .05       0
Bank Sta=5013.9,5018.6
XS Rating Curve= 0 ,0
Exp/Cntr=0.3,0.1

Type RM Length L Ch R = 1 ,3262    ,280,280,280
BEGIN DESCRIPTION:
Elm 01 86 3262.45
END DESCRIPTION:
XS GIS Cut Line= 3
      1620875.51      6794824.53      1620753.11      6795185.22
      1620725.76      6795308.94
#Sta/Elev= 30
  4622.1 1907.75  4703.2 1906.97  4720.8 1907.24  4734.6 1907.93    4766 1906.33
  4805.3 1905.26  4879.2 1904.84  4900.3 1905.19  4910.9 1904.78  4917.7 1903.74
    4923 1903.43  4954.4 1902.41  4963.7 1901.43  4985.8 1901.08  4999.5 1899.52
  4999.8 1899.02  5003.8 1899.02  5004.2 1899.52  5019.3 1900.61  5026.3  1901.7
  5057.1 1901.22  5062.9 1900.45  5068.1 1901.95  5077.5 1901.13  5087.8 1900.89
    5098 1901.16  5106.6 1904.14  5111.7    1905  5118.5 1907.21  5129.7 1907.94
#Mann= 3 ,-1 , 0
  4622.1     .05       0  4999.5     .05       0  5004.2     .05       0
Bank Sta=4999.5,5004.2
XS Rating Curve= 0 ,0
Exp/Cntr=0.3,0.1

Type RM Length L Ch R = 1 ,2982    ,275,275,275
BEGIN DESCRIPTION:
Elm 01 86 2981.7
END DESCRIPTION:
XS GIS Cut Line= 3
       1620611.4      6794580.76      1620604.88      6794988.79
      1620598.37      6795392.46
#Sta/Elev= 30
  4592.6 1911.79  4619.8 1909.14  4639.8 1908.87  4659.8  1909.5  4677.5 1907.98
  4699.9 1906.98  4739.9 1907.63  4759.9 1905.48  4779.9 1904.99  4909.9  1904.1
  4929.9 1904.34  4939.9  1905.3  4949.9 1904.01  4989.9 1901.94  4997.8 1900.47
  5002.8 1900.47  5007.5 1897.88  5007.9 1897.38  5011.9 1897.38  5012.2 1897.88
  5019.9  1899.5  5169.9 1901.36  5179.9 1901.42  5199.9 1899.86  5209.9 1900.75
  5229.9 1901.05  5239.9 1899.81  5259.9 1899.74  5309.9 1902.83  5404.4 1903.67
#Mann= 3 ,-1 , 0
  4592.6     .05       0  5007.5     .05       0  5012.2     .05       0
Bank Sta=5007.5,5012.2
XS Rating Curve= 0 ,0
Exp/Cntr=0.3,0.1

Type RM Length L Ch R = 1 ,2707    ,321,321,321
BEGIN DESCRIPTION:
Elm 01 86 2706.55
END DESCRIPTION:
XS GIS Cut Line= 3
      1620355.74      6794762.35      1620360.95      6795090.46
      1620465.12       6795552.3
#Sta/Elev= 30
  4676.8 1904.01  4742.5 1903.73  4772.5 1904.69  4782.5 1904.31  4842.5 1897.87
  4900.1 1897.26  4900.4 1896.76  4904.5 1896.76  4904.9 1897.26  4946.4 1898.02
  4982.5  1897.3  5022.9 1897.44  5053.7 1898.27  5074.2  1900.5  5095.7 1900.94
  5115.2 1900.56  5138.9 1901.06  5145.9 1900.54  5182.1 1900.07  5197.2 1900.17
  5230.5 1901.76  5258.7 1901.25    5310 1901.36  5360.2  1902.7  5371.5  1903.7
  5381.7 1904.05    5433 1903.71  5451.7 1904.41  5463.7 1905.69  5478.4 1905.56
#Mann= 3 ,-1 , 0
  4676.8     .05       0  4900.1     .05       0  4904.9     .05       0
Bank Sta=4900.1,4904.9
XS Rating Curve= 0 ,0
Exp/Cntr=0.3,0.1

Type RM Length L Ch R = 1 ,2386    ,365,365,365
BEGIN DESCRIPTION:
Elm 01 86 2386.13
END DESCRIPTION:
XS GIS Cut Line= 3
      1619980.75      6794965.47      1620098.79      6795146.02
      1620320.51      6795521.89
#Sta/Elev= 30
  4785.9 1903.25  4804.8 1903.38  4812.8 1903.91  4819.9 1903.21  4862.1 1901.34
  4877.2 1901.14  4898.3  1901.5  4907.4 1901.04  4913.4 1900.08  4934.5 1898.08
  4956.2 1895.34  4970.7 1895.47  4977.4 1895.05  4977.8 1894.55  4981.9 1894.55
  4982.2 1895.05    4992 1896.39  4999.8  1896.3  5028.3 1897.37  5038.1 1897.33
  5050.4 1895.73  5059.6 1895.45    5124 1895.31  5182.5 1896.77  5212.9  1898.4
  5219.6 1899.13  5315.2 1899.48  5358.1 1901.77    5387 1901.23    5438 1901.84
#Mann= 3 ,-1 , 0
  4785.9     .05       0  4977.4     .05       0  4982.2     .05       0
Bank Sta=4977.4,4982.2
XS Rating Curve= 0 ,0
Exp/Cntr=0.3,0.1

Type RM Length L Ch R = 1 ,2021    ,417,417,417
BEGIN DESCRIPTION:
Elm 01 86 2021.13
END DESCRIPTION:
XS GIS Cut Line= 4
      1619930.39       6795092.2      1619947.75      6795330.04
      1620039.77      6795453.31      1620242.35      6795733.81
#Sta/Elev= 30
  4607.8 1901.42  4733.9 1898.85  4814.1 1896.43  4864.6 1896.25  4879.2 1896.68
  4893.6 1896.02    4900 1894.48  4920.9 1895.97  4929.2 1895.06  4935.5 1895.77
  4950.1 1895.94  4964.7 1895.31  4983.1 1892.09  4983.5 1891.59  4987.6 1891.59
    4988 1892.09  4993.5 1893.58  5006.3 1894.07  5014.8 1896.05    5021 1894.96
  5035.7 1897.37  5050.4 1898.25    5086 1899.17  5165.7 1899.75  5207.4 1901.26
  5272.4  1901.4  5301.8  1902.8  5314.3 1903.91  5328.9 1903.31  5346.1 1903.48
#Mann= 3 ,-1 , 0
  4607.8     .05       0  4983.1     .03       0    4988     .05       0
Bank Sta=4983.1,4988
XS Rating Curve= 0 ,0
Exp/Cntr=0.3,0.1

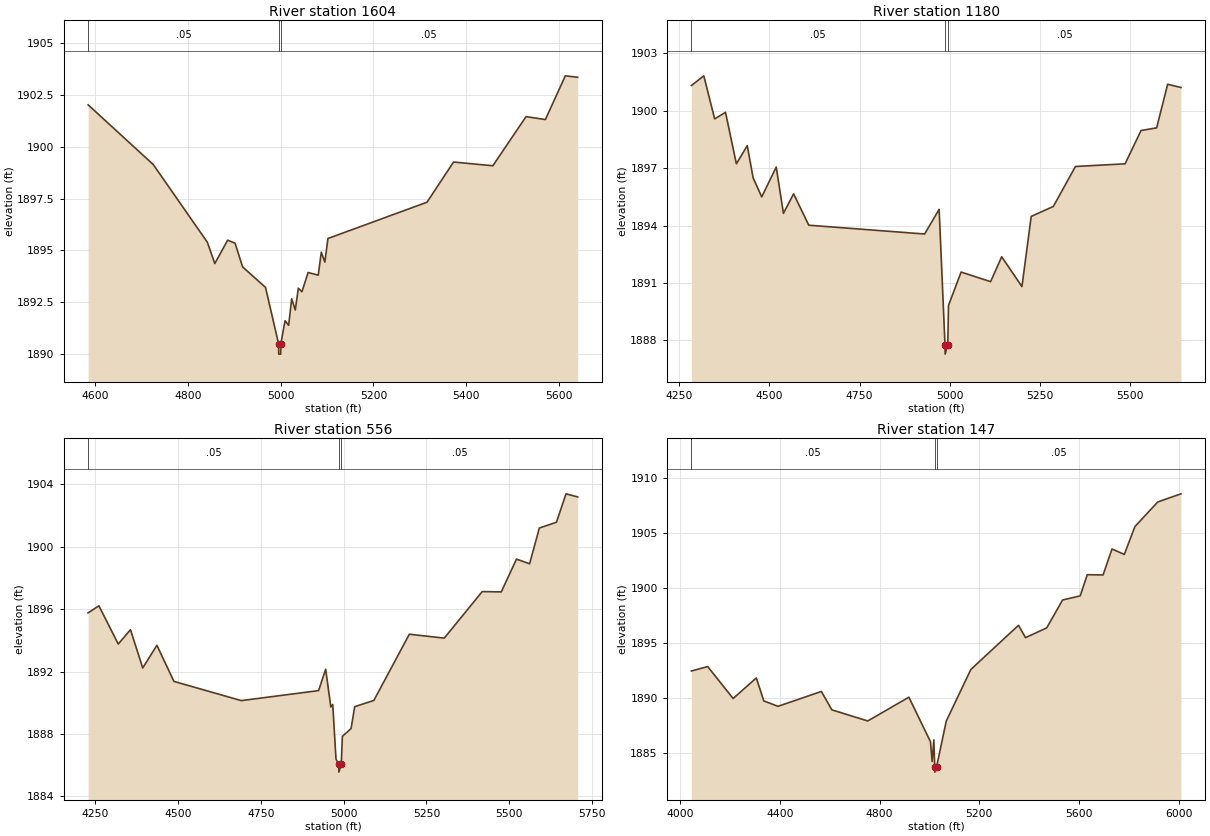
Type RM Length L Ch R = 1 ,1604    ,424,424,424
BEGIN DESCRIPTION:
Elm 01 86 1603.63
END DESCRIPTION:
XS GIS Cut Line= 3
      1619871.35      6795074.87      1619671.71      6795441.15
      1620159.53      6795850.85
#Sta/Elev= 30
  4585.6 1902.02  4725.8 1899.14  4842.3 1895.39  4858.4 1894.36    4886 1895.49
  4902.1 1895.34  4918.2  1894.2  4967.6 1893.21  4995.7 1890.49    4996 1889.99
  5000.2 1889.99  5000.6 1890.49  5009.6  1891.6  5017.4 1891.38  5023.9 1892.66
  5031.7 1892.12  5038.2 1893.17    5046    1893  5059.3 1893.93  5081.1  1893.8
  5087.7 1894.91  5095.4 1894.43    5102 1895.57  5315.3 1897.32  5372.5 1899.26
  5457.1 1899.08  5528.6 1901.45  5570.3 1901.31  5613.2 1903.42  5639.8 1903.35
#Mann= 3 ,-1 , 0
  4585.6     .05       0  4995.7     .05       0  5000.6     .05       0
Bank Sta=4995.7,5000.6
XS Rating Curve= 0 ,0
Exp/Cntr=0.3,0.1

Type RM Length L Ch R = 1 ,1180    ,624,624,624
BEGIN DESCRIPTION:
Elm 01 86 1180.07
END DESCRIPTION:
XS GIS Cut Line= 3
      1618740.74      6795677.91       1619451.7      6795740.42
      1620080.94      6795875.62
#Sta/Elev= 30
  4283.9 1901.32  4318.3 1901.83  4348.4 1899.58  4378.5 1899.92  4408.6 1897.23
  4438.8 1898.18    4455  1896.5  4478.9  1895.5  4519.1 1897.06  4539.1 1894.64
  4567.3 1895.66  4609.4 1894.02  4930.6 1893.56  4970.8 1894.85    4987 1887.78
  4987.5 1887.28  4994.7 1887.78  4996.8 1889.83  5031.7 1891.57  5113.5 1891.07
  5144.2 1892.37  5200.4 1890.81    5226 1894.48  5287.4    1895  5348.7 1897.09
  5486.4 1897.23  5530.6 1898.97  5573.8 1899.11  5604.4 1901.39  5641.2 1901.22
#Mann= 3 ,-1 , 0
  4283.9     .05       0    4987     .05       0  4994.7     .05       0
Bank Sta=4987,4994.7
XS Rating Curve= 0 ,0
Exp/Cntr=0.3,0.1

Type RM Length L Ch R = 1 ,556     ,409,409,409
BEGIN DESCRIPTION:
Elm 01 86 556.39
END DESCRIPTION:
XS GIS Cut Line= 3
      1618842.77      6795855.87      1619502.48      6796250.83
      1620147.02      6795955.69
#Sta/Elev= 30
  4228.7 1895.76  4261.2 1896.21  4319.6 1893.76  4356.5 1894.68  4393.5 1892.23
  4436.3 1893.68  4487.7 1891.37    4691 1890.14  4924.4 1890.78  4945.8 1892.15
  4961.3 1889.73  4967.1 1889.89  4976.9  1886.4    4985 1886.06  4985.5 1885.56
  4992.7 1886.06  4996.2 1887.85  5022.4 1888.35  5033.4 1889.75  5091.2 1890.15
  5198.3 1894.39  5303.7 1894.14  5418.3 1897.12  5475.8  1897.1  5521.8  1899.2
  5561.3  1898.9  5590.8 1901.19  5642.4 1901.56  5671.3 1903.38  5706.5 1903.18
#Mann= 3 ,-1 , 0
  4228.7     .05       0    4985     .07       0  4992.7     .05       0
Bank Sta=4985,4992.7
XS Rating Curve= 0 ,0
Exp/Cntr=0.3,0.1

Type RM Length L Ch R = 1 ,147     ,0,0,0
BEGIN DESCRIPTION:
Elm 01 86 971.844
END DESCRIPTION:
XS GIS Cut Line= 3
       1618810.5      6796089.91      1619604.08      6796622.08
      1620345.22       6795937.1
#Sta/Elev= 30
  4044.5 1892.43  4110.1 1892.83    4212 1889.93  4305.1  1891.8  4335.1 1889.71
  4392.1 1889.22  4566.2 1890.57  4608.2  1888.9  4752.3 1887.89  4917.4 1890.05
    5004    1886  5010.7 1884.21  5017.5 1886.17    5021 1883.74  5021.5 1883.24
  5028.7 1883.74  5067.4 1887.88  5166.1 1892.57  5357.2 1896.58  5385.5 1895.46
  5470.6 1896.35  5534.1 1898.88    5605 1899.26  5633.3 1901.18  5696.8 1901.16
  5732.5 1903.52  5781.9 1903.02  5824.4 1905.55  5916.2 1907.79  6009.2 1908.53
#Mann= 3 ,-1 , 0
  4044.5     .05       0    5021     .04       0  5028.7     .05       0
Bank Sta=5021,5028.7
XS Rating Curve= 0 ,0
Exp/Cntr=0.3,0.1

Chan Stop Cuts=-1
Use User Specified Reach Order=0
Composite Channel Slope=5