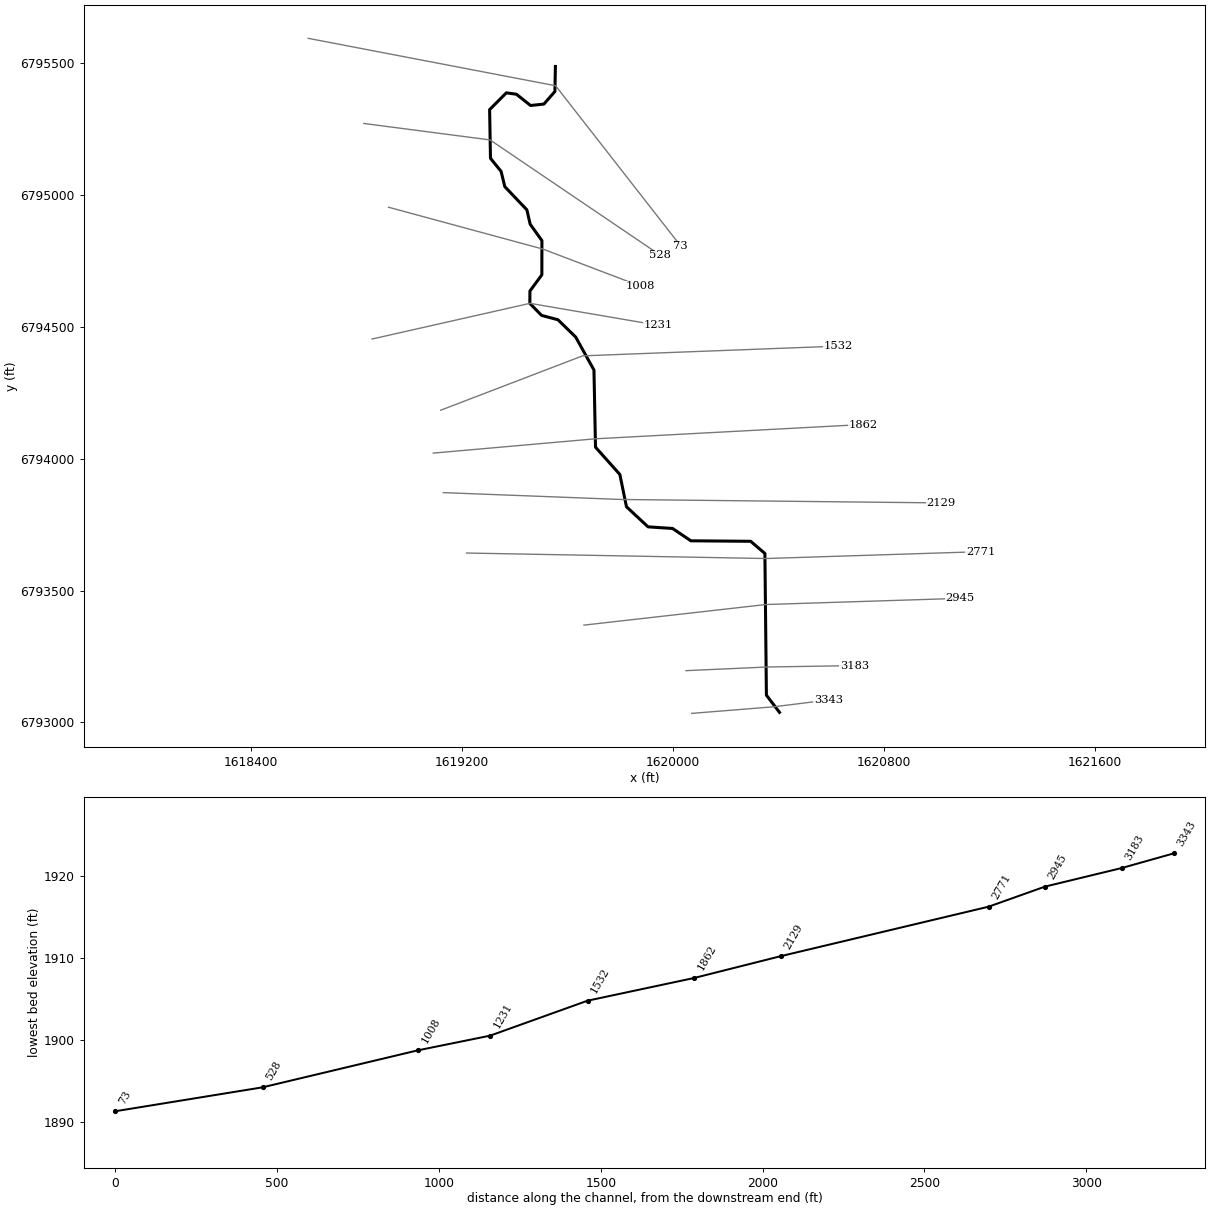
--- Elm 01 87.prj (project) ---

Proj Title=Elm 01 87 Base Level Engineering
Current Plan=p01
Default Exp/Contr=0.3,0.1
English Units
Geom File=g01
Flow File=f01
Plan File=p01
BEGIN DESCRIPTION:
Elm 01 87
END DESCRIPTION:

--- Elm 01 87.p01 (plan) ---

Plan Title=Multiple Run
Short Identifier=Multiple
Geom File=g01
Flow File=f01
Subcritical Flow
K Sum by GR= 0
Std Step Tol= 0.01
Critical Tol= 0.01
Num of Std Step Trials= 20
Max Error Tol= 0.3
Flow Tol Ratio= 0.001
Split Flow NTrial= 30
Split Flow Tol= 0.02
Split Flow Ratio= 0.02
Log Output Level= 0
Friction Slope Method= 1
Unsteady Friction Slope Method= 2
Unsteady Bridges Friction Slope Method= 1
Parabolic Critical Depth
Global Vel Dist=  1 , 1 , 1
Global Log Level= 0
CheckData=True
Encroach Param= -1, 0, 0, 0
BEGIN DESCRIPTION:
Multiple Run
END DESCRIPTION:

--- Elm 01 87.f01 (steady flow) ---

Flow Title=Multiple
Number of Profiles=7
Profile Names=10-year,25-year,50-year,1pct_min,100-year,1pct_plu,500-year
River Rch & RM= Elm 01 87,Reach-1,3343
     372     537     680     534     856    1180    1380
River Rch & RM= Elm 01 87,Reach-1,2129
     386     560     711     561     899    1240    1460
Boundary for River Rch & Prof#=Elm 01 87,Reach-1,1
Up Type=0
Dn Type=3
Dn Slope=0.001
Boundary for River Rch & Prof#=Elm 01 87,Reach-1,2
Up Type=0
Dn Type=3
Dn Slope=0.001
Boundary for River Rch & Prof#=Elm 01 87,Reach-1,3
Up Type=0
Dn Type=3
Dn Slope=0.001
Boundary for River Rch & Prof#=Elm 01 87,Reach-1,4
Up Type=0
Dn Type=3
Dn Slope=0.001
Boundary for River Rch & Prof#=Elm 01 87,Reach-1,5
Up Type=0
Dn Type=3
Dn Slope=0.001
Boundary for River Rch & Prof#=Elm 01 87,Reach-1,6
Up Type=0
Dn Type=3
Dn Slope=0.001
Boundary for River Rch & Prof#=Elm 01 87,Reach-1,7
Up Type=0
Dn Type=3
Dn Slope=0.001

--- Elm 01 87.g01 (geometry) ---

Geom Title=Existing Conditions

River Reach=Elm 01 87,Reach-1
Reach XY= 30
      1620405.00      6793038.00      1620355.36      6793103.15
      1620349.66      6793640.74      1620295.59      6793686.87
      1620068.92      6793688.68      1619999.43      6793735.53
      1619906.48      6793741.61      1619824.61      6793817.80
      1619799.46      6793940.42      1619707.07      6794043.86
      1619701.25      6794336.45      1619632.01      6794461.52
      1619564.68      6794527.22      1619502.39      6794543.75
      1619458.04      6794589.42      1619458.33      6794636.22
      1619503.61      6794697.66      1619503.81      6794827.50
      1619459.22      6794889.75      1619446.84      6794944.05
      1619363.16      6795031.95      1619348.86      6795090.17
      1619308.75      6795139.55      1619305.48      6795324.31
      1619368.89      6795387.96      1619407.16      6795382.62
      1619460.75      6795339.91      1619511.38      6795345.32
      1619553.12      6795393.09      1619555.00      6795488.00

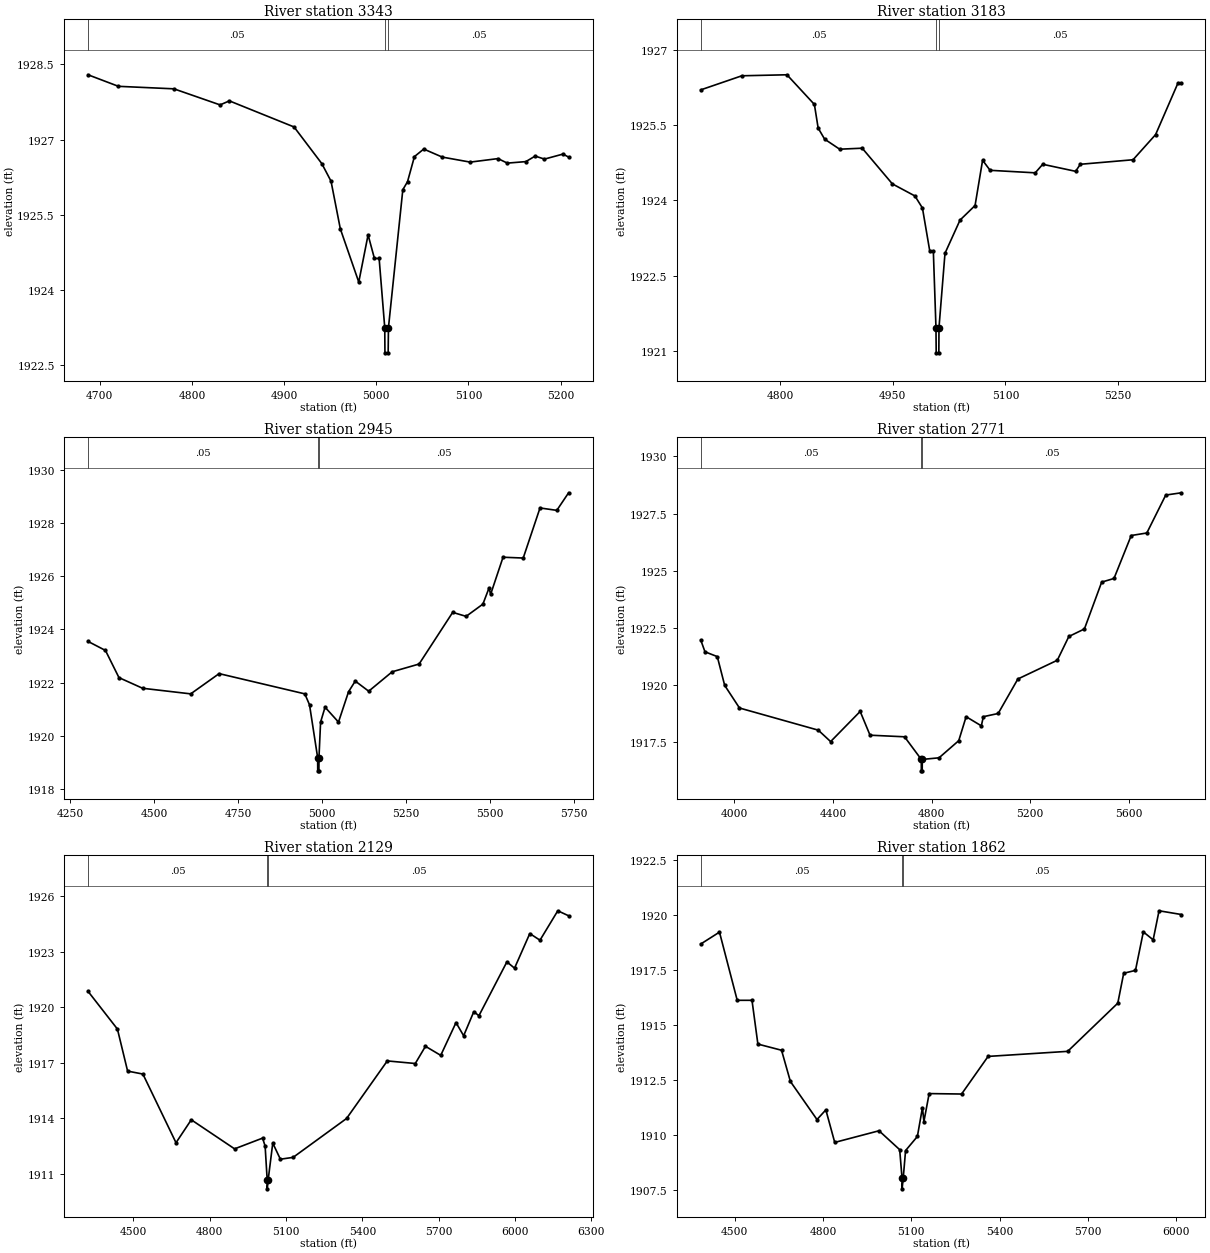
Type RM Length L Ch R = 1,3343,160,160,160
BEGIN DESCRIPTION:
Elm 01 87 2952.512
END DESCRIPTION:
XS GIS Cut Line= 3
      1620072.12      6793034.11      1620383.92      6793059.12
      1620591.02      6793084.90
#Sta/Elev= 30
  4687.2 1928.29  4720.2 1928.06  4780.4 1928.01  4830.5 1927.69  4840.6 1927.77
  4910.8 1927.25  4940.9 1926.52  4950.9 1926.17  4961.0 1925.22  4981.0 1924.16
  4991.1 1925.10  4998.0 1924.63  5003.1 1924.63  5009.2 1923.25  5009.4 1922.75
  5012.9 1922.75  5013.2 1923.25  5028.8 1926.00  5033.9 1926.16  5041.4 1926.66
  5051.5 1926.81  5071.6 1926.65  5101.9 1926.55  5132.1 1926.62  5142.2 1926.53
  5162.3 1926.56  5172.4 1926.67  5182.5 1926.61  5202.6 1926.71  5208.7 1926.65
#Mann=3,-1,0
  4687.2    0.05       0  5009.2    0.03       0  5013.2    0.05       0
Bank Sta=5009.2,5013.2
Exp/Cntr=0.3,0.1

Type RM Length L Ch R = 1,3183,238,238,238
BEGIN DESCRIPTION:
Elm 01 87 3182.55
END DESCRIPTION:
XS GIS Cut Line= 3
      1620050.49      6793196.15      1620359.48      6793210.04
      1620689.34      6793215.24
#Sta/Elev= 30
  4694.8 1926.20  4749.4 1926.48  4809.4 1926.50  4845.9 1925.91  4850.9 1925.44
  4859.5 1925.22  4879.5 1925.02  4909.5 1925.04  4949.6 1924.33  4979.6 1924.09
  4989.6 1923.85  4999.4 1922.99  5004.1 1922.99  5007.6 1921.47  5007.9 1920.97
  5011.4 1920.97  5011.6 1921.47  5019.6 1922.95  5039.6 1923.61  5059.6 1923.90
  5069.6 1924.80  5079.6 1924.60  5139.6 1924.55  5149.6 1924.72  5193.3 1924.58
  5199.6 1924.72  5269.7 1924.81  5299.7 1925.31  5329.3 1926.33  5334.0 1926.33
#Mann=3,-1,0
  4694.8    0.05       0  5007.6    0.03       0  5011.6    0.05       0
Bank Sta=5007.6,5011.6
Exp/Cntr=0.3,0.1

Type RM Length L Ch R = 1,2945,174,174,174
BEGIN DESCRIPTION:
Elm 01 87 2945.32
END DESCRIPTION:
XS GIS Cut Line= 3
      1619663.34      6793368.89      1620353.40      6793447.01
      1621090.16      6793470.44
#Sta/Elev= 30
  4303.5 1923.55  4355.5 1923.21  4395.7 1922.19  4466.2 1921.79  4609.4 1921.58
  4694.1 1922.34  4949.3 1921.58  4963.3 1921.17  4987.5 1919.19  4987.8 1918.69
  4991.3 1918.69  4991.5 1919.19  4996.3 1920.52  5009.6 1921.08  5049.6 1920.52
  5079.6 1921.66  5099.6 1922.06  5139.6 1921.68  5209.7 1922.41  5289.7 1922.70
  5389.8 1924.64  5429.8 1924.49  5479.8 1924.95  5497.9 1925.55  5502.9 1925.32
  5539.8 1926.71  5599.9 1926.68  5649.9 1928.56  5699.9 1928.47  5735.1 1929.13
#Mann=3,-1,0
  4303.5    0.05       0  4987.5    0.05       0  4991.5    0.05       0
Bank Sta=4987.5,4991.5
Exp/Cntr=0.3,0.1

Type RM Length L Ch R = 1,2771,642,642,642
BEGIN DESCRIPTION:
Elm 01 87 2770.84
END DESCRIPTION:
XS GIS Cut Line= 3
      1619217.97      6793642.33      1620353.40      6793621.49
      1621168.47      6793647.53
#Sta/Elev= 30
  3863.3 1921.96  3880.3 1921.45  3930.3 1921.24  3960.3 1919.98  4020.4 1918.99
  4340.4 1918.02  4390.4 1917.52  4510.4 1918.84  4550.4 1917.80  4690.5 1917.73
  4758.5 1916.74  4758.7 1916.24  4762.2 1916.24  4762.5 1916.74  4830.5 1916.81
  4910.5 1917.56  4940.5 1918.61  5002.2 1918.21  5010.5 1918.61  5070.6 1918.75
  5150.6 1920.26  5310.7 1921.08  5357.5 1922.12  5420.7 1922.45  5490.8 1924.50
  5540.8 1924.66  5610.8 1926.54  5674.1 1926.65  5750.9 1928.31  5814.4 1928.41
#Mann=3,-1,0
  3863.3    0.05       0  4758.5    0.03       0  4762.5    0.05       0
Bank Sta=4758.5,4762.5
Exp/Cntr=0.3,0.1

Type RM Length L Ch R = 1,2129,267,267,267
BEGIN DESCRIPTION:
Elm 01 87 2128.66
END DESCRIPTION:
XS GIS Cut Line= 3
      1619129.47      6793871.49      1619806.53      6793845.45
      1621017.50      6793832.43
#Sta/Elev= 30
  4321.9 1920.87  4437.5 1918.83  4477.5 1916.56  4537.6 1916.40  4667.7 1912.69
  4727.7 1913.93  4897.9 1912.36  5007.9 1912.94  5017.9 1912.51  5025.9 1910.70
  5026.1 1910.20  5030.0 1910.70  5047.9 1912.67  5077.9 1911.80  5127.9 1911.90
  5337.9 1914.00  5498.0 1917.11  5608.0 1916.97  5648.0 1917.90  5708.0 1917.41
  5768.0 1919.18  5798.0 1918.47  5838.0 1919.77  5858.0 1919.55  5968.0 1922.46
  5998.0 1922.12  6058.0 1923.99  6098.0 1923.63  6168.0 1925.22  6210.5 1924.95
#Mann=3,-1,0
  4321.9    0.05       0  5025.9    0.05       0  5030.0    0.05       0
Bank Sta=5025.9,5030
Exp/Cntr=0.3,0.1

Type RM Length L Ch R = 1,1862,330,330,330
BEGIN DESCRIPTION:
Elm 01 87 1861.89
END DESCRIPTION:
XS GIS Cut Line= 3
      1619091.71      6794021.34      1619705.87      6794075.60
      1620720.77      6794129.81
#Sta/Elev= 30
  4384.8 1918.67  4448.3 1919.21  4508.6 1916.11  4558.8 1916.11  4578.8 1914.12
  4659.2 1913.84  4689.3 1912.42  4779.6 1910.69  4809.7 1911.13  4839.9 1909.65
  4990.4 1910.18  5060.6 1909.32  5068.5 1908.04  5068.8 1907.54  5072.7 1908.04
  5080.6 1909.28  5120.7 1909.92  5137.9 1911.23  5142.9 1910.60  5160.7 1911.87
  5270.9 1911.85  5361.0 1913.56  5631.4 1913.79  5801.6 1915.98  5821.7 1917.34
  5861.7 1917.47  5888.4 1919.22  5921.8 1918.86  5941.8 1920.18  6017.7 1920.01
#Mann=3,-1,0
  4384.8    0.05       0  5068.5    0.05       0  5072.7    0.05       0
Bank Sta=5068.5,5072.7
Exp/Cntr=0.3,0.1

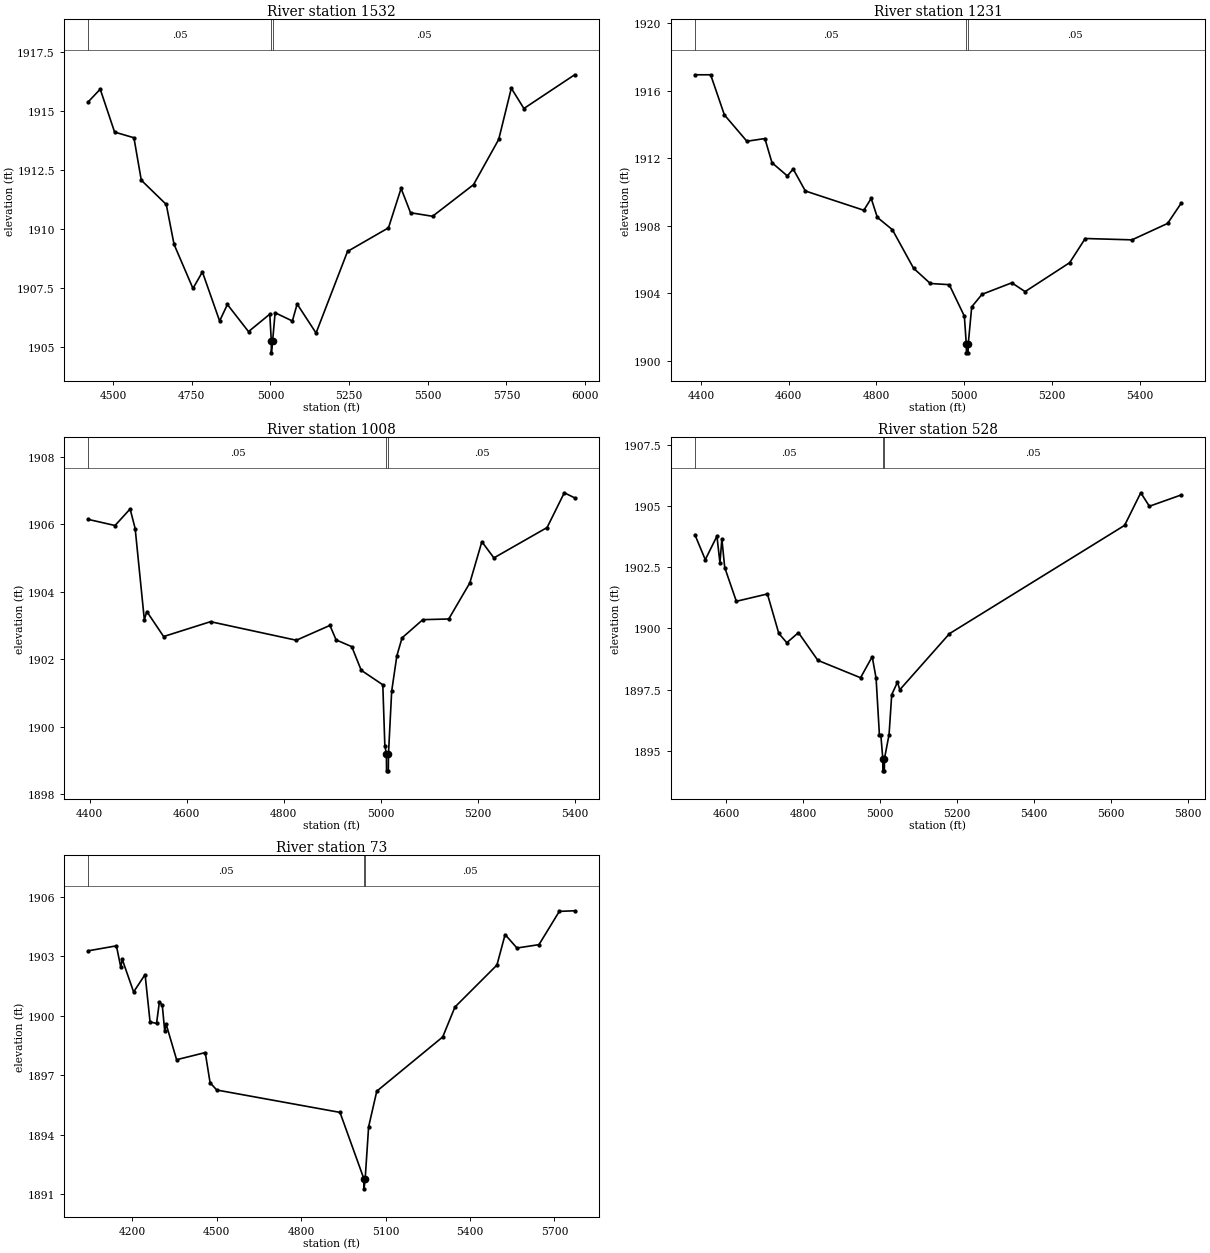
Type RM Length L Ch R = 1,1532,301,301,301
BEGIN DESCRIPTION:
Elm 01 87 1532.41
END DESCRIPTION:
XS GIS Cut Line= 3
      1619119.98      6794184.12      1619658.13      6794390.27
      1620626.04      6794427.16
#Sta/Elev= 30
  4421.6 1915.41  4459.1 1915.94  4504.8 1914.12  4566.2 1913.88  4589.6 1912.08
  4669.0 1911.05  4693.7 1909.36  4753.8 1907.49  4783.8 1908.19  4838.5 1906.11
  4863.2 1906.81  4930.3 1905.66  4997.9 1906.40  5002.7 1905.26  5002.9 1904.76
  5006.9 1905.26  5014.8 1906.46  5069.7 1906.11  5084.8 1906.83  5144.9 1905.60
  5244.9 1909.06  5375.0 1910.06  5415.1 1911.73  5445.1 1910.70  5515.1 1910.55
  5645.2 1911.89  5725.3 1913.81  5765.3 1915.98  5805.3 1915.12  5966.5 1916.55
#Mann=3,-1,0
  4421.6    0.05       0  5002.7    0.05       0  5006.9    0.05       0
Bank Sta=5002.7,5006.9
Exp/Cntr=0.3,0.1

Type RM Length L Ch R = 1,1231,223,223,223
BEGIN DESCRIPTION:
Elm 01 87 1230.75
END DESCRIPTION:
XS GIS Cut Line= 3
      1618859.46      6794454.07      1619458.40      6794589.48
      1619945.36      6794506.15
#Sta/Elev= 30
  4386.3 1916.93  4422.2 1916.93  4453.5 1914.56  4504.8 1913.00  4545.8 1913.16
  4562.0 1911.73  4597.0 1910.95  4610.3 1911.36  4638.0 1910.06  4771.3 1908.92
  4788.1 1909.62  4802.1 1908.50  4836.4 1907.77  4884.7 1905.49  4922.8 1904.59
  4966.0 1904.52  5000.4 1902.66  5004.9 1900.99  5005.2 1900.49  5008.9 1900.49
  5009.2 1900.99  5017.2 1903.21  5040.7 1903.95  5108.5 1904.63  5138.9 1904.11
  5240.4 1905.82  5275.9 1907.25  5382.4 1907.17  5463.6 1908.14  5494.4 1909.33
#Mann=3,-1,0
  4386.3    0.05       0  5004.9    0.05       0  5009.2    0.05       0
Bank Sta=5004.9,5009.2
Exp/Cntr=0.3,0.1

Type RM Length L Ch R = 1,1008,480,480,480
BEGIN DESCRIPTION:
Elm 01 87 1007.78
END DESCRIPTION:
XS GIS Cut Line= 3
      1618921.97      6794954.06      1619507.88      6794795.21
      1619877.68      6794654.58
#Sta/Elev= 30
  4397.2 1906.15  4452.1 1905.97  4483.2 1906.46  4493.6 1905.88  4512.5 1903.18
  4517.7 1903.42  4552.3 1902.68  4649.0 1903.12  4826.0 1902.57  4895.3 1903.01
  4908.0 1902.58  4940.3 1902.38  4959.8 1901.68  5004.3 1901.25  5008.5 1899.45
  5011.7 1899.20  5012.0 1898.70  5015.7 1898.70  5016.0 1899.20  5022.6 1901.06
  5033.3 1902.11  5044.0 1902.64  5086.8 1903.18  5140.3 1903.20  5183.8 1904.27
  5208.6 1905.49  5233.4 1905.01  5343.1 1905.91  5378.6 1906.94  5399.9 1906.79
#Mann=3,-1,0
  4397.2    0.05       0  5011.7    0.05       0  5016.0    0.05       0
Bank Sta=5011.7,5016
Exp/Cntr=0.3,0.1

Type RM Length L Ch R = 1,528,455,455,455
BEGIN DESCRIPTION:
Elm 01 87 527.79
END DESCRIPTION:
XS GIS Cut Line= 3
      1618828.20      6795271.78      1619307.36      6795209.28
      1619953.20      6794771.77
#Sta/Elev= 30
  4519.3 1903.82  4546.3 1902.80  4576.6 1903.76  4584.4 1902.67  4589.4 1903.64
  4596.8 1902.48  4627.0 1901.10  4707.7 1901.40  4737.3 1899.79  4758.1 1899.41
  4788.4 1899.82  4838.8 1898.69  4949.7 1897.98  4980.0 1898.84  4990.1 1897.96
  4998.8 1895.63  5002.5 1895.63  5007.5 1894.68  5007.8 1894.18  5011.6 1894.18
  5011.9 1894.68  5023.8 1895.66  5030.7 1897.29  5045.7 1897.80  5051.7 1897.49
  5180.8 1899.78  5635.8 1904.20  5677.8 1905.53  5700.2 1904.98  5782.6 1905.44
#Mann=3,-1,0
  4519.3    0.05       0  5007.5    0.05       0  5011.9    0.05       0
Bank Sta=5007.5,5011.9
Exp/Cntr=0.3,0.1

Type RM Length L Ch R = 1,73,0,0,0
BEGIN DESCRIPTION:
Elm 01 87 2032.875
END DESCRIPTION:
XS GIS Cut Line= 3
      1618617.29      6795594.69      1619555.71      6795414.87
      1620030.64      6794806.49
#Sta/Elev= 30
  4044.5 1903.28  4144.0 1903.53  4159.5 1902.45  4164.6 1902.85  4205.1 1901.20
  4245.8 1902.08  4263.5 1899.69  4286.5 1899.61  4296.7 1900.70  4306.9 1900.53
  4315.6 1899.22  4320.7 1899.57  4357.8 1897.78  4459.6 1898.14  4476.7 1896.62
  4500.4 1896.25  4938.2 1895.12  5023.3 1891.76  5023.6 1891.26  5027.7 1891.76
  5039.9 1894.39  5068.9 1896.19  5303.2 1898.93  5346.6 1900.44  5495.8 1902.56
  5524.8 1904.10  5566.9 1903.42  5645.1 1903.59  5717.4 1905.27  5771.8 1905.30
#Mann=3,-1,0
  4044.5    0.05       0  5023.3    0.05       0  5027.7    0.05       0
Bank Sta=5023.3,5027.7
Exp/Cntr=0.3,0.1

Chan Stop Cuts=-1