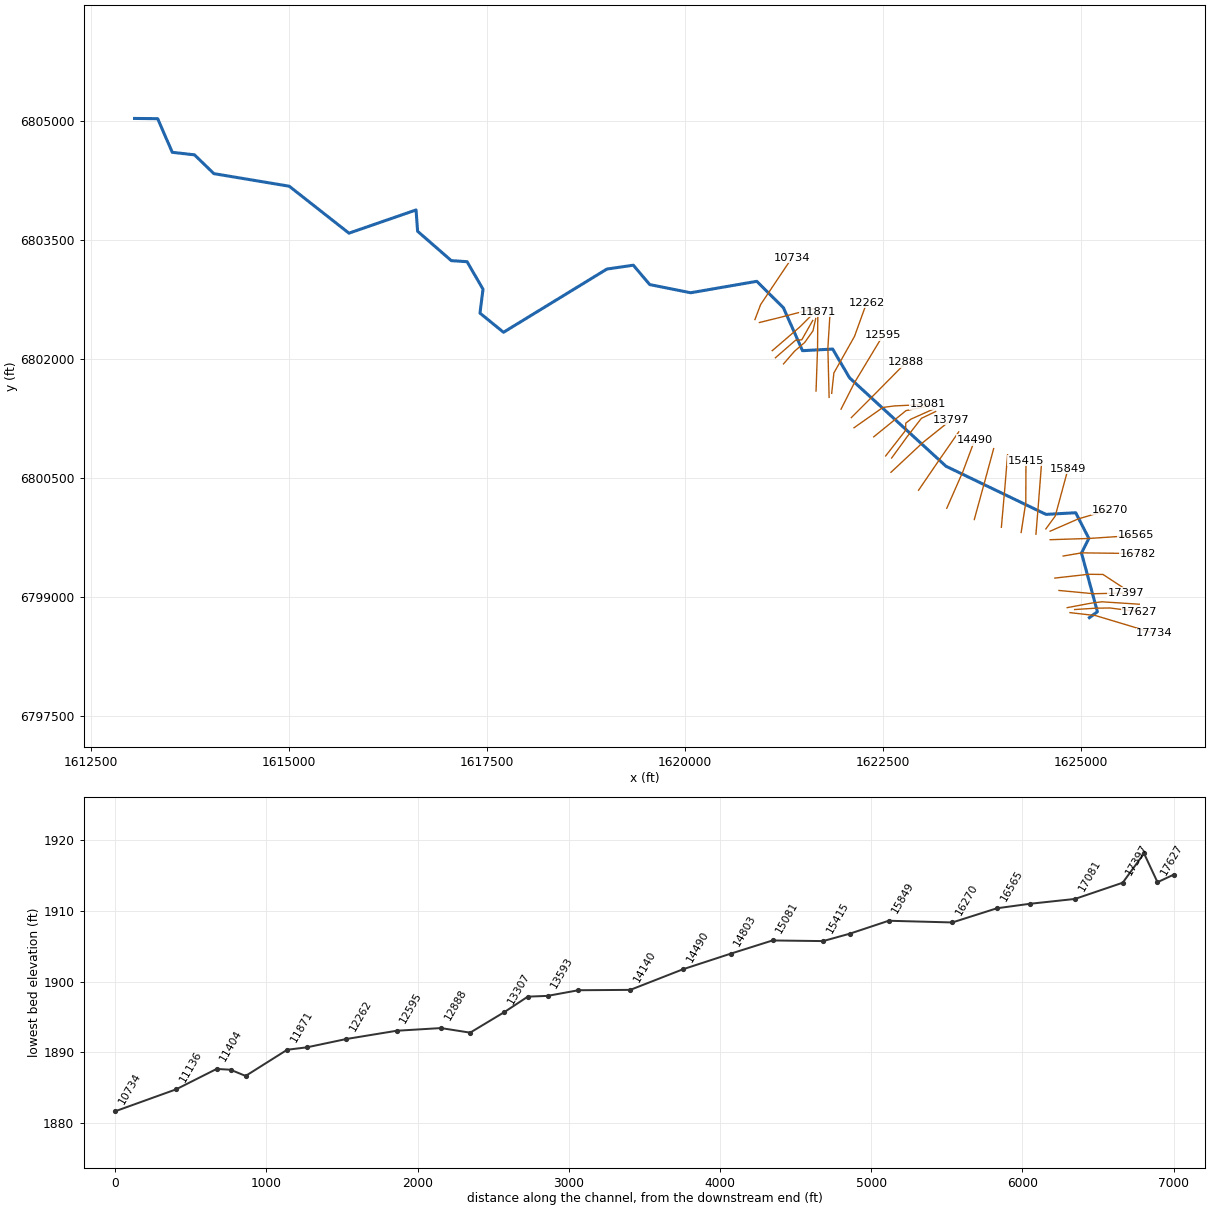
--- Elm 01 88.prj (project) ---

Proj Title=Elm 01 88 Base Level Engineering
Current Plan=p01
Default Exp/Contr=0.3,0.1
English Units
Geom File=g01
Flow File=f01
Plan File=p01
BEGIN DESCRIPTION:
Elm 01 88
END DESCRIPTION:

--- Elm 01 88.p01 (plan) ---

Plan Title=Multiple Run
Short Identifier=Multiple
Geom File=g01
Flow File=f01
Subcritical Flow
K Sum by GR= 0
Std Step Tol= 0.01
Critical Tol= 0.01
Num of Std Step Trials= 20
Max Error Tol= 0.3
Flow Tol Ratio= 0.001
Split Flow NTrial= 30
Split Flow Tol= 0.02
Split Flow Ratio= 0.02
Log Output Level= 0
Friction Slope Method= 1
Unsteady Friction Slope Method= 2
Unsteady Bridges Friction Slope Method= 1
Parabolic Critical Depth
Global Vel Dist=  1 , 1 , 1
Global Log Level= 0
CheckData=True
Encroach Param= -1, 0, 0, 0
BEGIN DESCRIPTION:
Multiple Run
END DESCRIPTION:

--- Elm 01 88.f01 (steady flow) ---

Flow Title=Multiple
Number of Profiles=7
Profile Names=10-year,25-year,50-year,1pct_min,100-year,1pct_plu,500-year
River Rch & RM= Elm 01 88,Reach-1,17734
     225     312     383     292     468     644     709
River Rch & RM= Elm 01 88,Reach-1,16270
     398     567     711     553     886    1220    1390
River Rch & RM= Elm 01 88,Reach-1,13797
     444     633     794     616     987    1360    1550
Boundary for River Rch & Prof#=Elm 01 88,Reach-1,1
Up Type=0
Dn Type=3
Dn Slope=0.001
Boundary for River Rch & Prof#=Elm 01 88,Reach-1,2
Up Type=0
Dn Type=3
Dn Slope=0.001
Boundary for River Rch & Prof#=Elm 01 88,Reach-1,3
Up Type=0
Dn Type=3
Dn Slope=0.001
Boundary for River Rch & Prof#=Elm 01 88,Reach-1,4
Up Type=0
Dn Type=3
Dn Slope=0.001
Boundary for River Rch & Prof#=Elm 01 88,Reach-1,5
Up Type=0
Dn Type=3
Dn Slope=0.001
Boundary for River Rch & Prof#=Elm 01 88,Reach-1,6
Up Type=0
Dn Type=3
Dn Slope=0.001
Boundary for River Rch & Prof#=Elm 01 88,Reach-1,7
Up Type=0
Dn Type=3
Dn Slope=0.001

--- Elm 01 88.g01 (geometry) ---

Geom Title=Existing Conditions

River Reach=Elm 01 88,Reach-1
Reach XY= 30
      1625105.00      6798738.00      1625205.66      6798812.95
      1625005.38      6799553.28      1625097.90      6799738.00
      1624932.18      6800061.99      1624556.50      6800041.61
      1623295.29      6800648.75      1622078.06      6801764.67
      1621865.12      6802127.66      1621484.53      6802107.27
      1621243.89      6802648.05      1620907.45      6802982.54
      1620073.27      6802838.21      1619556.25      6802941.45
      1619349.02      6803186.08      1619015.48      6803137.07
      1617711.43      6802339.43      1617414.13      6802581.26
      1617452.65      6802882.48      1617251.46      6803230.19
      1617052.55      6803243.46      1616627.26      6803614.16
      1616607.59      6803883.03      1615760.94      6803590.25
      1615007.44      6804182.48      1614056.26      6804341.48
      1613811.67      6804578.70      1613531.16      6804610.56
      1613347.09      6805035.09      1613055.00      6805038.00

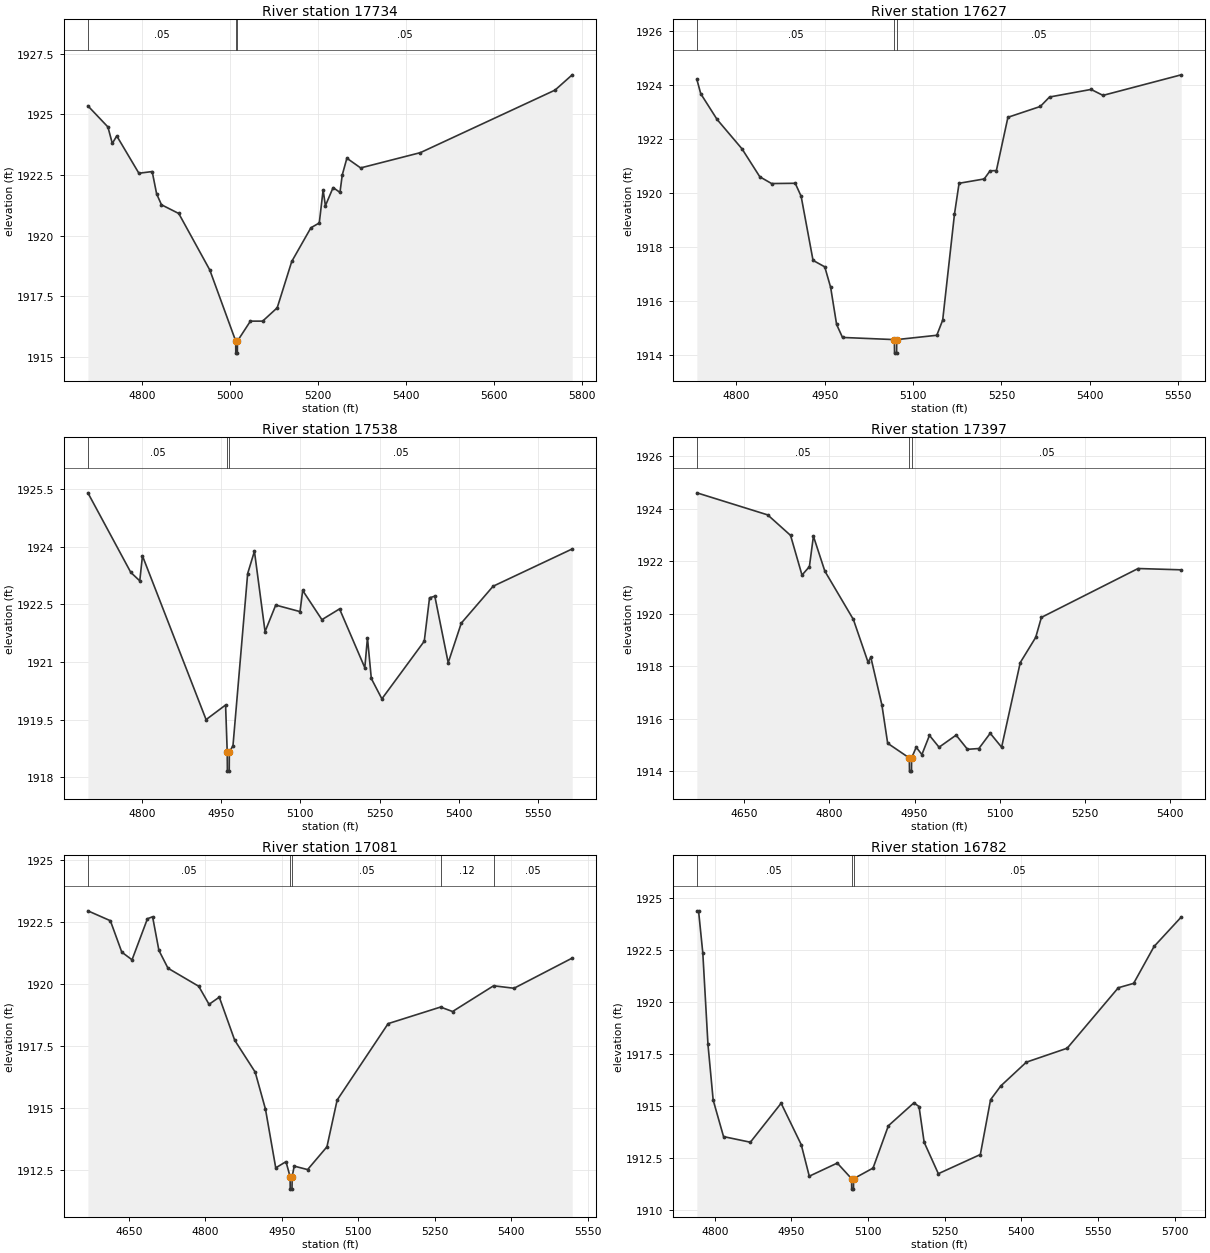
Type RM Length L Ch R = 1,17734,107,107,107
BEGIN DESCRIPTION:
Elm 01 88 17360.132
END DESCRIPTION:
XS GIS Cut Line= 3
      1624859.84      6798801.57      1625180.94      6798764.79
      1625925.37      6798541.16
#Sta/Elev= 30
  4676.8 1925.35  4722.3 1924.48  4732.3 1923.80  4742.4 1924.11  4792.7 1922.57
  4822.9 1922.64  4833.0 1921.72  4844.0 1921.27  4883.3 1920.91  4953.8 1918.58
  5012.7 1915.65  5012.9 1915.15  5016.4 1915.15  5016.7 1915.65  5046.1 1916.47
  5073.9 1916.47  5107.0 1917.02  5140.0 1918.93  5183.5 1920.32  5202.6 1920.52
  5211.3 1921.88  5216.5 1921.23  5234.0 1921.98  5249.6 1921.78  5254.8 1922.50
  5265.3 1923.19  5296.6 1922.79  5432.3 1923.42  5738.3 1926.00  5777.3 1926.63
#Mann=3,-1,0
  4676.8    0.05       0  5012.7    0.05       0  5016.7    0.05       0
Bank Sta=5012.7,5016.7
Exp/Cntr=0.3,0.1

Type RM Length L Ch R = 1,17627,89,89,89
BEGIN DESCRIPTION:
Elm 01 88 17626.55
END DESCRIPTION:
XS GIS Cut Line= 4
      1624918.44      6798840.63      1625187.56      6798857.99
      1625365.51      6798860.16      1625736.61      6798812.42
#Sta/Elev= 30
  4733.2 1924.20  4739.8 1923.67  4767.5 1922.72  4809.9 1921.63  4840.0 1920.60
  4860.0 1920.35  4900.1 1920.36  4910.1 1919.88  4930.3 1917.51  4950.2 1917.27
  4960.2 1916.51  4970.3 1915.14  4980.3 1914.66  5068.3 1914.58  5068.6 1914.08
  5072.1 1914.08  5072.3 1914.58  5140.3 1914.74  5150.3 1915.30  5170.3 1919.22
  5178.1 1920.36  5220.7 1920.52  5230.7 1920.82  5241.4 1920.83  5261.0 1922.80
  5315.9 1923.20  5331.6 1923.55  5402.1 1923.83  5422.3 1923.61  5555.0 1924.37
#Mann=3,-1,0
  4733.2    0.05       0  5068.3    0.05       0  5072.3    0.05       0
Bank Sta=5068.3,5072.3
Exp/Cntr=0.3,0.1

Type RM Length L Ch R = 1,17538,141,141,141
BEGIN DESCRIPTION:
Elm 01 88 17538.02
END DESCRIPTION:
XS GIS Cut Line= 4
      1624825.16      6798864.50      1625124.63      6798920.92
      1625263.52      6798938.28      1625734.44      6798907.90
#Sta/Elev= 30
  4697.8 1925.40  4779.0 1923.33  4796.0 1923.11  4801.1 1923.76  4921.5 1919.50
  4958.4 1919.88  4961.5 1918.66  4961.8 1918.16  4965.3 1918.16  4965.5 1918.66
  4972.4 1918.82  5000.2 1923.30  5013.0 1923.88  5033.1 1921.79  5053.3 1922.48
  5099.3 1922.31  5104.3 1922.86  5140.7 1922.10  5174.1 1922.38  5221.9 1920.85
  5226.9 1921.63  5234.2 1920.57  5254.2 1920.04  5334.4 1921.54  5344.4 1922.67
  5354.4 1922.71  5379.7 1920.98  5404.5 1922.01  5464.7 1922.97  5614.4 1923.94
#Mann=3,-1,0
  4697.8    0.05       0  4961.5    0.05       0  4965.5    0.05       0
Bank Sta=4961.5,4965.5
Exp/Cntr=0.3,0.1

Type RM Length L Ch R = 1,17397,316,316,316
BEGIN DESCRIPTION:
Elm 01 88 17397.45
END DESCRIPTION:
XS GIS Cut Line= 3
      1624720.94      6799081.52      1625155.01      6799040.28
      1625570.80      6799048.94
#Sta/Elev= 30
  4567.2 1924.60  4691.8 1923.76  4732.0 1922.98  4752.1 1921.47  4765.1 1921.79
  4772.2 1922.95  4792.3 1921.62  4842.5 1919.78  4868.2 1918.16  4873.2 1918.34
  4892.7 1916.52  4902.8 1915.07  4940.9 1914.51  4941.2 1914.01  4944.7 1914.01
  4944.9 1914.51  4953.0 1914.92  4963.0 1914.64  4976.3 1915.37  4993.2 1914.92
  5023.2 1915.38  5043.2 1914.84  5063.2 1914.87  5083.2 1915.45  5103.2 1914.92
  5136.0 1918.14  5163.2 1919.10  5173.2 1919.86  5343.3 1921.72  5419.1 1921.67
#Mann=3,-1,0
  4567.2    0.05       0  4940.9    0.05       0  4944.9    0.05       0
Bank Sta=4940.9,4944.9
Exp/Cntr=0.3,0.1

Type RM Length L Ch R = 1,17081,299,299,299
BEGIN DESCRIPTION:
Elm 01 88 17081.28
END DESCRIPTION:
XS GIS Cut Line= 4
      1624668.91      6799237.76      1625094.25      6799285.51
      1625276.24      6799283.37      1625560.45      6799097.14
#Sta/Elev= 30
  4569.8 1922.96  4613.9 1922.56  4636.3 1921.29  4656.4 1920.98  4686.6 1922.64
  4696.7 1922.72  4709.1 1921.36  4726.9 1920.64  4787.2 1919.91  4807.4 1919.18
  4827.5 1919.47  4857.7 1917.73  4897.9 1916.44  4918.1 1914.94  4938.2 1912.57
  4958.3 1912.82  4966.4 1912.21  4966.6 1911.71  4970.1 1911.71  4970.4 1912.21
  4974.4 1912.64  5000.7 1912.50  5038.6 1913.42  5058.6 1915.31  5158.6 1918.40
  5261.4 1919.07  5285.0 1918.89  5365.4 1919.93  5405.5 1919.83  5519.6 1921.05
#Mann=5,-1,0
  4569.8    0.05       0  4966.4    0.05       0  4970.4    0.05       0
  5261.4    0.12       0  5365.4    0.05       0
Bank Sta=4966.4,4970.4
Exp/Cntr=0.3,0.1

Type RM Length L Ch R = 1,16782,217,217,217
BEGIN DESCRIPTION:
Elm 01 88 16782.04
END DESCRIPTION:
XS GIS Cut Line= 3
      1624773.59      6799515.97      1625007.96      6799555.90
      1625718.05      6799547.22
#Sta/Elev= 30
  4764.9 1924.37  4768.2 1924.37  4776.5 1922.35  4786.6 1917.96  4796.8 1915.29
  4817.1 1913.54  4869.6 1913.27  4929.8 1915.14  4969.2 1913.15  4984.9 1911.64
  5039.7 1912.27  5067.7 1911.52  5067.9 1911.02  5071.4 1911.02  5071.7 1911.52
  5109.7 1912.03  5139.7 1914.06  5189.7 1915.16  5199.7 1914.98  5209.7 1913.27
  5237.5 1911.76  5319.7 1912.68  5339.7 1915.31  5359.7 1915.97  5409.7 1917.11
  5489.7 1917.78  5589.7 1920.68  5619.7 1920.89  5659.7 1922.66  5712.8 1924.07
#Mann=3,-1,0
  4764.9    0.05       0  5067.7    0.03       0  5071.7    0.05       0
Bank Sta=5067.7,5071.7
Exp/Cntr=0.3,0.1

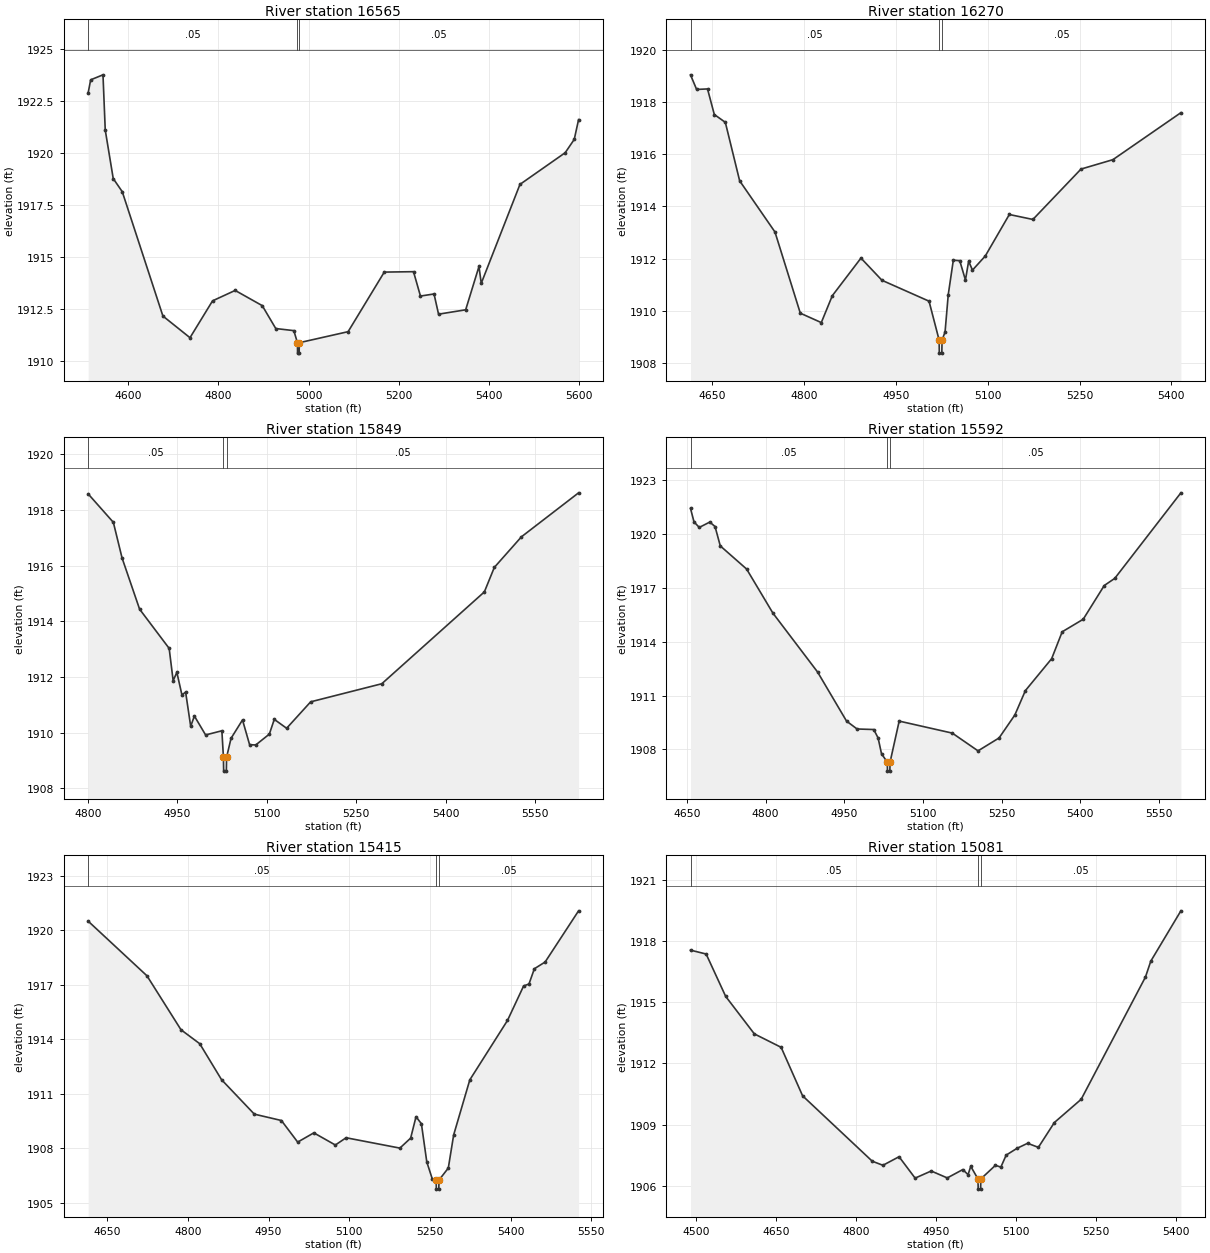
Type RM Length L Ch R = 1,16565,295,295,295
BEGIN DESCRIPTION:
Elm 01 88 16565.24
END DESCRIPTION:
XS GIS Cut Line= 3
      1624609.49      6799721.88      1625097.37      6799737.50
      1625694.61      6799777.43
#Sta/Elev= 30
  4511.6 1922.89  4517.1 1923.51  4544.4 1923.75  4549.4 1921.10  4567.1 1918.77
  4587.1 1918.14  4677.2 1912.17  4737.2 1911.13  4787.2 1912.90  4837.3 1913.40
  4897.3 1912.67  4927.3 1911.57  4967.3 1911.47  4975.3 1910.89  4975.6 1910.39
  4979.1 1910.39  4979.3 1910.89  5087.6 1911.42  5167.7 1914.28  5232.5 1914.30
  5247.9 1913.13  5278.0 1913.23  5288.0 1912.26  5348.1 1912.47  5377.6 1914.55
  5382.6 1913.74  5468.4 1918.49  5568.6 1920.01  5588.7 1920.65  5598.3 1921.60
#Mann=3,-1,0
  4511.6    0.05       0  4975.3    0.05       0  4979.3    0.05       0
Bank Sta=4975.3,4979.3
Exp/Cntr=0.3,0.1

Type RM Length L Ch R = 1,16270,421,421,421
BEGIN DESCRIPTION:
Elm 01 88 16270.36
END DESCRIPTION:
XS GIS Cut Line= 3
      1624609.56      6799829.53      1624963.69      6799984.03
      1625361.50      6800101.64
#Sta/Elev= 30
  4614.4 1919.04  4624.4 1918.48  4642.2 1918.50  4653.3 1917.52  4671.3 1917.22
  4694.7 1914.98  4752.4 1913.02  4793.8 1909.91  4828.1 1909.55  4846.1 1910.58
  4892.9 1912.02  4927.2 1911.17  5004.1 1910.37  5020.6 1908.88  5020.9 1908.38
  5025.0 1908.38  5025.4 1908.88  5030.3 1909.19  5035.5 1910.62  5043.8 1911.94
  5054.3 1911.92  5063.6 1911.18  5068.8 1911.90  5075.1 1911.56  5096.0 1912.10
  5135.3 1913.69  5173.8 1913.50  5252.4 1915.43  5304.5 1915.79  5415.6 1917.59
#Mann=3,-1,0
  4614.4    0.05       0  5020.6    0.05       0  5025.4    0.05       0
Bank Sta=5020.6,5025.4
Exp/Cntr=0.3,0.1

Type RM Length L Ch R = 1,15849,257,257,257
BEGIN DESCRIPTION:
Elm 01 88 15849.43
END DESCRIPTION:
XS GIS Cut Line= 3
      1624555.56      6799858.37      1624673.59      6800019.79
      1624836.77      6800620.45
#Sta/Elev= 30
  4800.5 1918.58  4842.7 1917.56  4857.3 1916.28  4886.7 1914.44  4936.3 1913.03
  4943.0 1911.87  4949.2 1912.17  4957.7 1911.36  4963.9 1911.46  4972.4 1910.23
  4978.6 1910.60  4997.4 1909.92  5024.7 1910.07  5027.3 1909.12  5027.7 1908.62
  5032.2 1908.62  5032.6 1909.12  5040.1 1909.80  5059.3 1910.46  5071.2 1909.57
  5081.5 1909.56  5104.3 1909.95  5112.6 1910.48  5133.3 1910.16  5173.6 1911.11
  5292.9 1911.76  5464.9 1915.06  5481.6 1915.94  5527.1 1917.04  5622.9 1918.62
#Mann=3,-1,0
  4800.5    0.05       0  5027.3    0.03       0  5032.6    0.05       0
Bank Sta=5027.3,5032.6
Exp/Cntr=0.3,0.1

Type RM Length L Ch R = 1,15592,177,177,177
BEGIN DESCRIPTION:
Elm 01 88 15592.43
END DESCRIPTION:
XS GIS Cut Line= 3
      1624430.27      6799791.34      1624458.48      6800136.37
      1624504.00      6800723.73
#Sta/Elev= 30
  4656.7 1921.44  4663.4 1920.69  4673.4 1920.38  4693.5 1920.68  4703.5 1920.43
  4713.5 1919.35  4763.7 1918.06  4813.9 1915.60  4899.0 1912.32  4954.3 1909.58
  4974.4 1909.14  5006.2 1909.11  5014.5 1908.64  5021.0 1907.76  5032.0 1907.29
  5032.4 1906.79  5036.9 1906.79  5037.3 1907.29  5054.7 1909.58  5156.0 1908.91
  5205.1 1907.92  5245.2 1908.64  5275.3 1909.92  5295.4 1911.28  5345.5 1913.06
  5365.6 1914.56  5405.7 1915.26  5445.8 1917.14  5465.9 1917.54  5592.0 1922.31
#Mann=3,-1,0
  4656.7    0.05       0  5032.0    0.03       0  5037.3    0.05       0
Bank Sta=5032,5037.3
Exp/Cntr=0.3,0.1

Type RM Length L Ch R = 1,15415,334,334,334
BEGIN DESCRIPTION:
Elm 01 88 15415.25
END DESCRIPTION:
XS GIS Cut Line= 3
      1624243.63      6799812.99      1624302.23      6800192.80
      1624304.40      6800720.19
#Sta/Elev= 30
  4614.7 1920.50  4724.0 1917.49  4787.2 1914.52  4822.1 1913.75  4862.6 1911.77
  4923.6 1909.87  4973.9 1909.52  5004.2 1908.33  5034.2 1908.84  5074.2 1908.17
  5094.2 1908.57  5194.2 1908.00  5214.2 1908.55  5224.2 1909.73  5234.2 1909.34
  5244.2 1907.24  5254.2 1906.32  5261.6 1906.24  5262.0 1905.74  5266.5 1905.74
  5266.9 1906.24  5284.2 1906.90  5294.2 1908.73  5324.2 1911.76  5394.2 1915.03
  5424.2 1916.93  5434.2 1917.04  5444.2 1917.88  5464.2 1918.25  5526.4 1921.07
#Mann=3,-1,0
  4614.7    0.05       0  5261.6    0.03       0  5266.9    0.05       0
Bank Sta=5261.6,5266.9
Exp/Cntr=0.3,0.1

Type RM Length L Ch R = 1,15081,278,278,278
BEGIN DESCRIPTION:
Elm 01 88 15080.53
END DESCRIPTION:
XS GIS Cut Line= 3
      1623994.08      6799878.85      1624039.21      6800390.97
      1624072.10      6800794.23
#Sta/Elev= 30
  4490.1 1917.56  4519.4 1917.37  4556.0 1915.29  4609.7 1913.45  4659.9 1912.79
  4700.1 1910.41  4830.6 1907.20  4850.6 1907.00  4880.8 1907.42  4910.9 1906.37
  4941.0 1906.72  4971.1 1906.38  5000.2 1906.79  5010.1 1906.54  5015.1 1906.95
  5028.6 1906.33  5029.1 1905.83  5033.6 1905.83  5034.0 1906.33  5061.4 1907.00
  5071.5 1906.91  5081.5 1907.50  5101.6 1907.83  5121.6 1908.08  5141.8 1907.88
  5171.8 1909.10  5222.0 1910.24  5342.4 1916.24  5352.4 1917.02  5408.8 1919.49
#Mann=3,-1,0
  4490.1    0.05       0  5028.6    0.05       0  5034.0    0.05       0
Bank Sta=5028.6,5034
Exp/Cntr=0.3,0.1

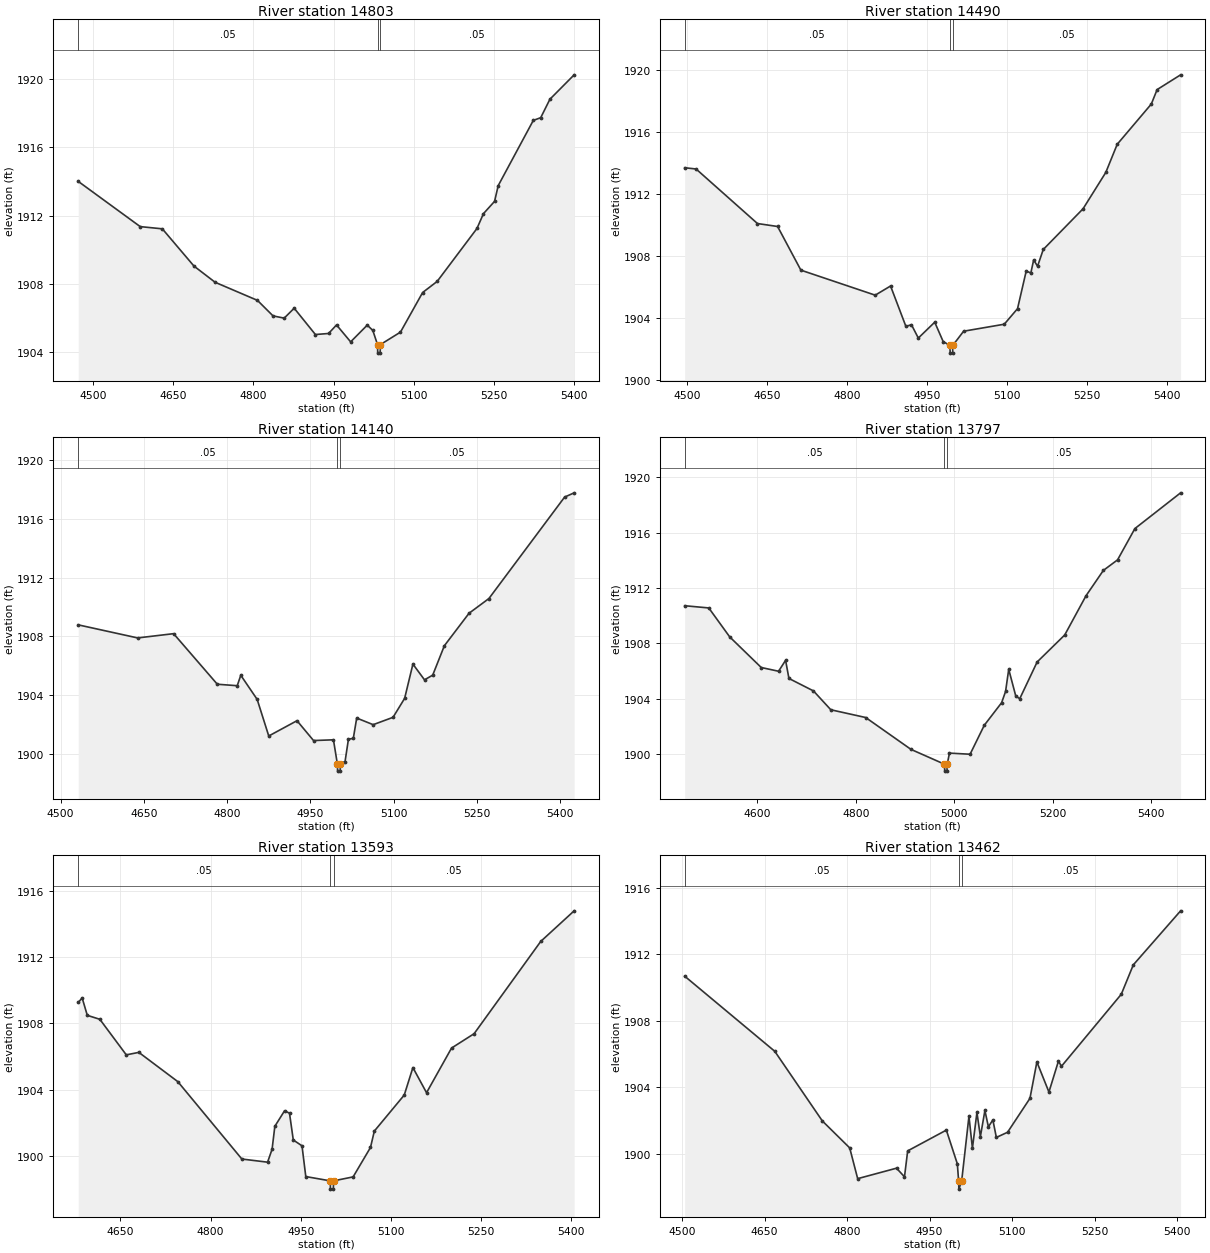
Type RM Length L Ch R = 1,14803,313,313,313
BEGIN DESCRIPTION:
Elm 01 88 14803.38
END DESCRIPTION:
XS GIS Cut Line= 3
      1623652.07      6799976.07      1623792.69      6800488.20
      1623896.84      6800871.83
#Sta/Elev= 30
  4471.9 1914.01  4588.0 1911.36  4629.4 1911.23  4688.6 1909.05  4728.2 1908.10
  4807.5 1907.04  4836.7 1906.13  4857.6 1906.00  4876.3 1906.58  4916.0 1905.04
  4940.6 1905.10  4955.6 1905.60  4982.0 1904.61  5013.1 1905.59  5023.5 1905.28
  5032.3 1904.45  5032.7 1903.95  5037.2 1903.95  5037.7 1904.45  5075.3 1905.18
  5116.8 1907.50  5144.0 1908.15  5218.5 1911.25  5230.7 1912.12  5251.5 1912.84
  5258.3 1913.76  5324.0 1917.58  5337.9 1917.74  5355.1 1918.82  5400.5 1920.25
#Mann=3,-1,0
  4471.9    0.05       0  5032.3    0.05       0  5037.7    0.05       0
Bank Sta=5032.3,5037.7
Exp/Cntr=0.3,0.1

Type RM Length L Ch R = 1,14490,350,350,350
BEGIN DESCRIPTION:
Elm 01 88 14490.1
END DESCRIPTION:
XS GIS Cut Line= 3
      1623304.83      6800118.39      1623507.96      6800580.21
      1623657.26      6800979.49
#Sta/Elev= 30
  4495.4 1913.69  4516.8 1913.61  4632.0 1910.10  4669.8 1909.91  4713.5 1907.10
  4853.0 1905.49  4881.8 1906.08  4910.6 1903.48  4921.0 1903.59  4933.9 1902.73
  4964.7 1903.75  4980.6 1902.50  4993.2 1902.26  4993.7 1901.76  4998.3 1901.76
  4998.7 1902.26  5018.9 1903.17  5095.2 1903.62  5120.1 1904.62  5136.4 1907.04
  5145.1 1906.92  5150.4 1907.76  5157.7 1907.35  5168.4 1908.43  5243.1 1911.05
  5285.8 1913.39  5307.2 1915.20  5371.2 1917.79  5382.1 1918.72  5426.2 1919.67
#Mann=3,-1,0
  4495.4    0.05       0  4993.2    0.05       0  4998.7    0.05       0
Bank Sta=4993.2,4998.7
Exp/Cntr=0.3,0.1

Type RM Length L Ch R = 1,14140,343,343,343
BEGIN DESCRIPTION:
Elm 01 88 14140.37
END DESCRIPTION:
XS GIS Cut Line= 3
      1622948.59      6800346.02      1623214.21      6800734.90
      1623455.54      6801082.14
#Sta/Elev= 30
  4531.6 1908.78  4638.7 1907.89  4703.5 1908.18  4782.3 1904.74  4818.2 1904.64
  4824.6 1905.35  4854.1 1903.71  4875.0 1901.22  4925.9 1902.26  4955.7 1900.91
  4991.6 1900.96  4998.6 1899.33  4999.1 1898.83  5003.7 1898.83  5004.1 1899.33
  5012.5 1899.48  5018.6 1901.00  5027.4 1901.06  5033.5 1902.44  5063.2 1901.99
  5099.0 1902.49  5119.9 1903.78  5134.8 1906.11  5155.7 1905.04  5170.5 1905.36
  5191.5 1907.36  5236.0 1909.57  5271.8 1910.57  5408.2 1917.47  5425.4 1917.76
#Mann=3,-1,0
  4531.6    0.05       0  4998.6    0.05       0  5004.1    0.05       0
Bank Sta=4998.6,5004.1
Exp/Cntr=0.3,0.1

Type RM Length L Ch R = 1,13797,204,204,204
BEGIN DESCRIPTION:
Elm 01 88 13796.9
END DESCRIPTION:
XS GIS Cut Line= 3
      1622600.99      6800572.63      1623000.28      6800945.88
      1623359.28      6801233.51
#Sta/Elev= 30
  4452.7 1910.72  4501.6 1910.56  4544.1 1908.47  4608.1 1906.26  4643.3 1905.99
  4657.5 1906.78  4664.3 1905.47  4714.1 1904.57  4749.3 1903.21  4820.1 1902.65
  4912.0 1900.35  4980.0 1899.28  4980.5 1898.78  4985.2 1898.78  4985.6 1899.28
  4990.1 1900.08  5032.0 1900.00  5060.8 1902.09  5096.0 1903.72  5104.0 1904.53
  5110.4 1906.13  5124.8 1904.19  5132.8 1904.01  5168.1 1906.66  5224.1 1908.61
  5267.3 1911.44  5302.5 1913.27  5331.3 1914.03  5366.5 1916.29  5459.3 1918.87
#Mann=3,-1,0
  4452.7    0.05       0  4980.0    0.05       0  4985.6    0.05       0
Bank Sta=4980,4985.6
Exp/Cntr=0.3,0.1

Type RM Length L Ch R = 1,13593,131,131,131
BEGIN DESCRIPTION:
Mapping XS 5b846963
END DESCRIPTION:
XS GIS Cut Line= 4
      1622609.48      6800753.07      1622803.95      6801020.46
      1622984.50      6801253.10      1623165.09      6801339.93
#Sta/Elev= 30
  4579.7 1909.27  4586.3 1909.54  4594.8 1908.49  4615.7 1908.25  4659.7 1906.10
  4680.6 1906.25  4745.5 1904.48  4852.1 1899.80  4894.9 1899.61  4902.4 1900.39
  4907.0 1901.78  4923.2 1902.72  4931.4 1902.57  4937.7 1900.95  4952.2 1900.60
  4958.5 1898.74  4999.2 1898.48  4999.6 1897.98  5004.3 1897.98  5004.8 1898.48
  5037.3 1898.72  5066.2 1900.50  5072.6 1901.49  5122.4 1903.67  5136.8 1905.33
  5159.5 1903.81  5201.1 1906.51  5238.7 1907.38  5349.6 1912.96  5405.2 1914.81
#Mann=3,-1,0
  4579.7    0.05       0  4999.2    0.05       0  5004.8    0.05       0
Bank Sta=4999.2,5004.8
Exp/Cntr=0.3,0.1

Type RM Length L Ch R = 1,13462,155,155,155
BEGIN DESCRIPTION:
Elm 01 88 13462.48
END DESCRIPTION:
XS GIS Cut Line= 5
      1622533.71      6800778.78      1622785.44      6801102.13
      1622787.61      6801193.27      1622852.71      6801243.19
      1623143.50      6801373.39
#Sta/Elev= 30
  4504.8 1910.68  4668.6 1906.16  4755.1 1901.97  4804.8 1900.35  4819.3 1898.50
  4889.9 1899.13  4904.4 1898.61  4910.2 1900.17  4980.5 1901.42  5000.5 1899.39
  5002.8 1898.37  5003.3 1897.87  5008.4 1898.37  5021.6 1902.25  5027.9 1900.33
  5036.1 1902.48  5042.4 1901.03  5050.6 1902.60  5056.9 1901.62  5065.1 1902.03
  5071.4 1900.98  5091.8 1901.29  5132.5 1903.33  5145.1 1905.52  5167.0 1903.71
  5184.3 1905.57  5189.8 1905.26  5298.5 1909.59  5320.4 1911.36  5406.4 1914.61
#Mann=3,-1,0
  4504.8    0.05       0  5002.8    0.05       0  5008.4    0.05       0
Bank Sta=5002.8,5008.4
Exp/Cntr=0.3,0.1

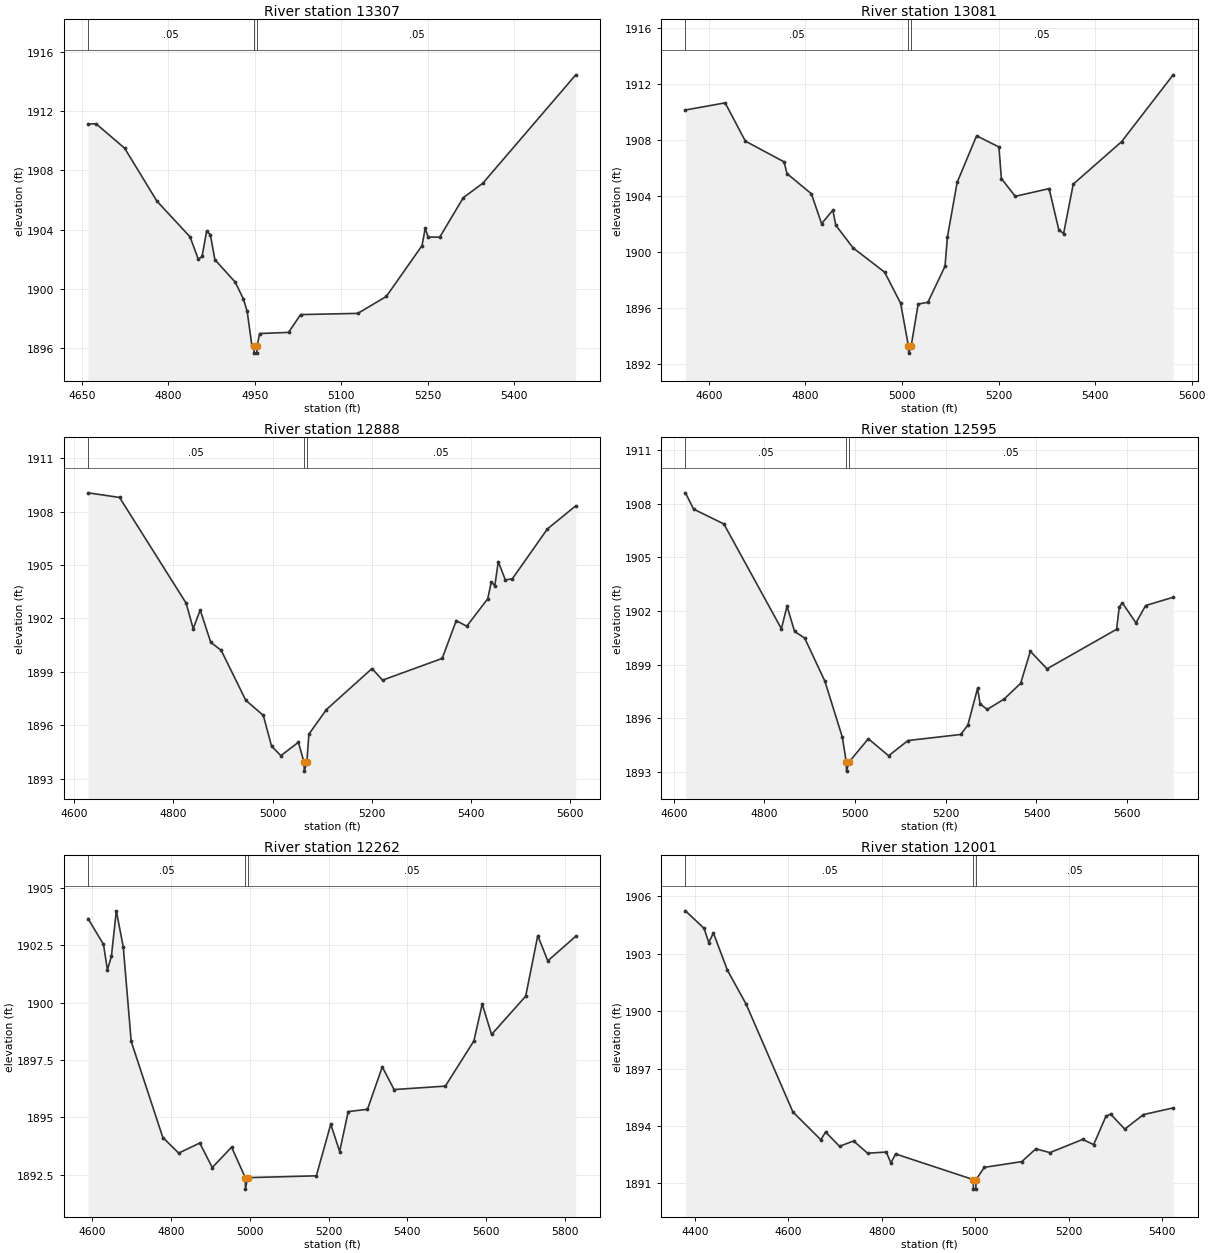
Type RM Length L Ch R = 1,13307,226,226,226
BEGIN DESCRIPTION:
Mapping XS e292ebc9
END DESCRIPTION:
XS GIS Cut Line= 3
      1622383.83      6801020.48      1622790.06      6801350.33
      1623106.06      6801416.31
#Sta/Elev= 30
  4660.9 1911.13  4674.8 1911.15  4724.4 1909.50  4780.4 1905.93  4837.9 1903.52
  4852.2 1902.01  4858.7 1902.20  4866.6 1903.90  4873.0 1903.68  4881.0 1901.98
  4916.2 1900.47  4930.5 1899.33  4937.0 1898.49  4944.9 1896.25  4948.5 1896.18
  4949.0 1895.68  4953.7 1895.68  4954.1 1896.18  4958.7 1897.00  5008.8 1897.08
  5029.7 1898.28  5128.8 1898.36  5178.3 1899.50  5240.3 1902.93  5245.8 1904.09
  5250.9 1903.51  5271.0 1903.50  5311.8 1906.16  5345.8 1907.14  5507.0 1914.45
#Mann=3,-1,0
  4660.9    0.05       0  4948.5    0.05       0  4954.1    0.05       0
Bank Sta=4948.5,4954.1
Exp/Cntr=0.3,0.1

Type RM Length L Ch R = 1,13081,193,193,193
BEGIN DESCRIPTION:
Elm 01 88 13081.12
END DESCRIPTION:
XS GIS Cut Line= 4
      1622134.36      6801134.65      1622498.98      6801390.76
      1622644.38      6801410.29      1623061.64      6801429.75
#Sta/Elev= 30
  4551.7 1910.12  4633.9 1910.63  4675.7 1907.90  4755.9 1906.42  4762.0 1905.58
  4812.5 1904.14  4833.6 1902.01  4856.9 1902.97  4863.0 1901.90  4898.8 1900.28
  4964.1 1898.55  4997.3 1896.33  5013.5 1893.27  5014.0 1892.77  5019.1 1893.27
  5033.6 1896.27  5053.8 1896.40  5089.2 1898.97  5094.2 1901.06  5114.3 1904.95
  5154.6 1908.28  5200.9 1907.48  5205.9 1905.23  5234.7 1903.96  5304.8 1904.51
  5324.8 1901.58  5334.8 1901.30  5354.8 1904.83  5454.9 1907.86  5561.7 1912.63
#Mann=3,-1,0
  4551.7    0.05       0  5013.5    0.03       0  5019.1    0.05       0
Bank Sta=5013.5,5019.1
Exp/Cntr=0.3,0.1

Type RM Length L Ch R = 1,12888,293,293,293
BEGIN DESCRIPTION:
Elm 01 88 12888.1
END DESCRIPTION:
XS GIS Cut Line= 3
      1622100.53      6801262.71      1622363.56      6801525.74
      1622793.22      6801960.61
#Sta/Elev= 30
  4627.8 1909.05  4691.3 1908.79  4825.6 1902.85  4839.8 1901.42  4853.9 1902.47
  4875.1 1900.66  4896.3 1900.20  4945.8 1897.40  4981.2 1896.55  4997.8 1894.82
  5016.6 1894.29  5051.9 1895.04  5063.2 1893.92  5063.7 1893.42  5068.9 1893.92
  5073.1 1895.50  5108.5 1896.88  5200.3 1899.18  5221.6 1898.53  5341.8 1899.75
  5370.1 1901.87  5391.3 1901.56  5433.7 1903.10  5440.8 1904.05  5447.9 1903.83
  5454.9 1905.19  5469.1 1904.16  5483.2 1904.22  5553.9 1907.02  5611.1 1908.32
#Mann=3,-1,0
  4627.8    0.05       0  5063.2    0.05       0  5068.9    0.05       0
Bank Sta=5063.2,5068.9
Exp/Cntr=0.3,0.1

Type RM Length L Ch R = 1,12595,333,333,333
BEGIN DESCRIPTION:
Elm 01 88 12595.41
END DESCRIPTION:
XS GIS Cut Line= 3
      1621970.80      6801369.22      1622140.08      6801703.45
      1622502.04      6802303.83
#Sta/Elev= 30
  4625.8 1908.60  4643.7 1907.69  4710.5 1906.86  4837.4 1901.00  4849.8 1902.26
  4866.5 1900.85  4888.7 1900.48  4933.3 1898.07  4971.9 1894.93  4980.6 1893.54
  4981.0 1893.04  4986.3 1893.54  5029.1 1894.85  5073.9 1893.90  5116.6 1894.75
  5233.1 1895.09  5248.6 1895.61  5270.0 1897.66  5275.8 1896.80  5291.3 1896.49
  5328.2 1897.06  5365.1 1897.95  5386.5 1899.74  5423.3 1898.76  5576.7 1900.97
  5582.6 1902.22  5589.6 1902.44  5619.4 1901.33  5640.8 1902.30  5701.5 1902.76
#Mann=3,-1,0
  4625.8    0.05       0  4980.6    0.03       0  4986.3    0.05       0
Bank Sta=4980.6,4986.3
Exp/Cntr=0.3,0.1

Type RM Length L Ch R = 1,12262,261,261,261
BEGIN DESCRIPTION:
Mapping XS 3ce124e2
END DESCRIPTION:
XS GIS Cut Line= 4
      1621852.56      6801569.06      1621880.34      6801826.02
      1622140.75      6802287.83      1622293.55      6802711.48
#Sta/Elev= 30
  4589.0 1903.66  4628.2 1902.54  4638.2 1901.43  4648.3 1902.01  4660.8 1904.00
  4678.5 1902.42  4698.6 1898.31  4779.0 1894.12  4819.3 1893.44  4872.8 1893.88
  4904.6 1892.81  4953.7 1893.70  4988.4 1892.37  4988.9 1891.87  4994.1 1892.37
  5169.0 1892.45  5205.6 1894.70  5228.2 1893.51  5249.9 1895.25  5298.9 1895.35
  5336.5 1897.20  5366.4 1896.21  5496.7 1896.36  5569.2 1898.33  5590.4 1899.94
  5614.1 1898.61  5700.8 1900.28  5731.5 1902.92  5756.9 1901.82  5828.0 1902.89
#Mann=3,-1,0
  4589.0    0.05       0  4988.4    0.05       0  4994.1    0.05       0
Bank Sta=4988.4,4994.1
Exp/Cntr=0.3,0.1

Type RM Length L Ch R = 1,12001,130,130,130
BEGIN DESCRIPTION:
Elm 01 88 12001.44
END DESCRIPTION:
XS GIS Cut Line= 3
      1621820.20      6801518.09      1621804.58      6802141.38
      1621830.62      6802561.49
#Sta/Elev= 30
  4379.6 1905.25  4419.5 1904.33  4429.5 1903.59  4439.5 1904.09  4469.5 1902.14
  4509.5 1900.37  4609.6 1894.73  4669.6 1893.27  4679.6 1893.68  4709.6 1892.93
  4739.6 1893.21  4769.6 1892.57  4809.6 1892.63  4819.6 1892.06  4829.6 1892.53
  4995.8 1891.19  4996.3 1890.69  5001.4 1890.69  5001.9 1891.19  5019.7 1891.83
  5099.9 1892.13  5129.9 1892.80  5160.0 1892.60  5230.1 1893.29  5253.8 1893.02
  5280.2 1894.51  5290.3 1894.61  5320.3 1893.83  5360.4 1894.59  5424.0 1894.94
#Mann=3,-1,0
  4379.6    0.05       0  4995.8    0.03       0  5001.9    0.05       0
Bank Sta=4995.8,5001.9
Exp/Cntr=0.3,0.1

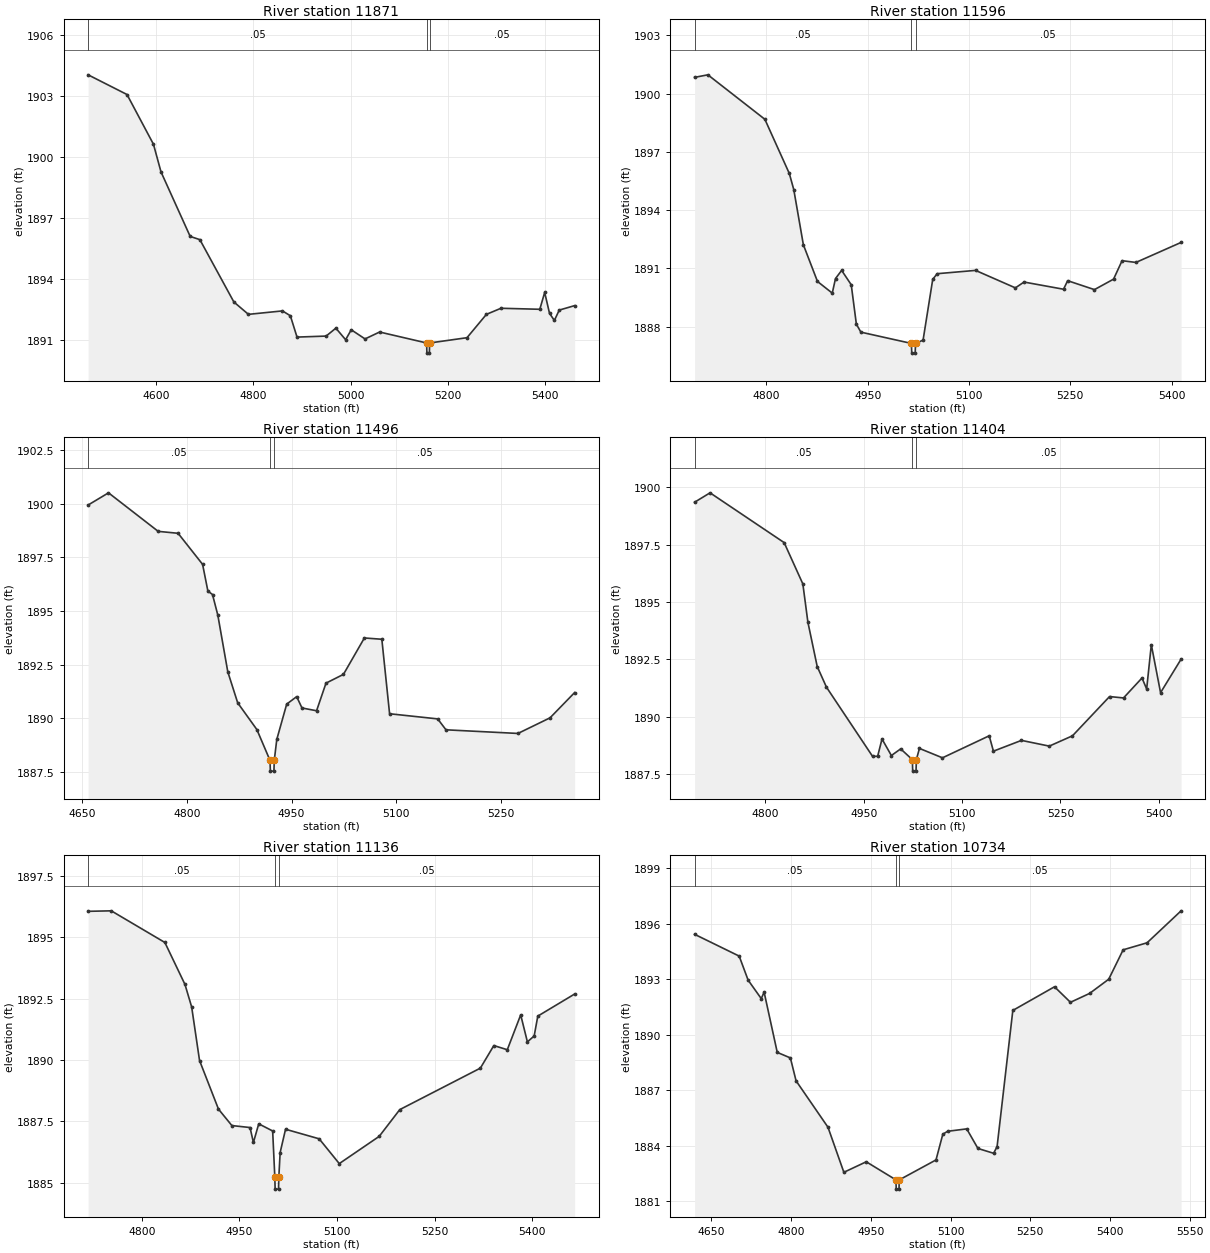
Type RM Length L Ch R = 1,11871,275,275,275
BEGIN DESCRIPTION:
Elm 01 88 11871.1
END DESCRIPTION:
XS GIS Cut Line= 3
      1621655.27      6801597.98      1621674.37      6802139.64
      1621677.84      6802599.73
#Sta/Elev= 30
  4459.5 1904.06  4539.6 1903.09  4594.1 1900.64  4609.6 1899.28  4669.7 1896.10
  4689.7 1895.94  4759.7 1892.87  4789.7 1892.26  4859.8 1892.43  4876.1 1892.19
  4889.8 1891.14  4949.8 1891.19  4969.8 1891.58  4989.9 1891.01  5001.5 1891.50
  5029.9 1891.05  5059.9 1891.39  5156.8 1890.85  5157.3 1890.35  5162.4 1890.35
  5162.9 1890.85  5239.9 1891.11  5279.9 1892.26  5309.9 1892.56  5389.9 1892.51
  5399.9 1893.34  5409.9 1892.31  5419.9 1891.96  5429.9 1892.47  5461.6 1892.69
#Mann=3,-1,0
  4459.5    0.05       0  5156.8    0.03       0  5162.9    0.05       0
Bank Sta=5156.8,5162.9
Exp/Cntr=0.3,0.1

Type RM Length L Ch R = 1,11596,100,100,100
BEGIN DESCRIPTION:
Mapping XS b2f380e5
END DESCRIPTION:
XS GIS Cut Line= 5
      1621244.95      6801940.64      1621383.81      6802100.33
      1621512.28      6802211.44      1621616.45      6802357.27
      1621651.12      6802513.28
#Sta/Elev= 30
  4693.7 1900.84  4713.4 1900.97  4797.8 1898.68  4834.0 1895.89  4840.6 1895.06
  4854.8 1892.22  4875.7 1890.33  4897.6 1889.73  4902.4 1890.48  4911.5 1890.90
  4925.7 1890.16  4933.3 1888.13  4940.0 1887.72  5014.8 1887.14  5015.3 1886.64
  5020.4 1886.64  5020.9 1887.14  5032.1 1887.31  5046.4 1890.44  5053.0 1890.73
  5109.8 1890.90  5168.8 1890.00  5181.6 1890.30  5240.1 1889.93  5246.2 1890.37
  5285.9 1889.91  5314.2 1890.45  5326.8 1891.40  5347.3 1891.31  5414.2 1892.34
#Mann=3,-1,0
  4693.7    0.05       0  5014.8    0.05       0  5020.9    0.05       0
Bank Sta=5014.8,5020.9
Exp/Cntr=0.3,0.1

Type RM Length L Ch R = 1,11496,92,92,92
BEGIN DESCRIPTION:
Elm 01 88 11496.05
END DESCRIPTION:
XS GIS Cut Line= 4
      1621143.12      6802018.12      1621400.06      6802242.07
      1621474.72      6802243.81      1621613.62      6802488.63
#Sta/Elev= 30
  4658.5 1899.95  4687.7 1900.52  4758.9 1898.72  4787.4 1898.63  4822.5 1897.18
  4830.1 1895.93  4836.7 1895.77  4844.3 1894.81  4858.6 1892.16  4872.8 1890.71
  4900.3 1889.46  4919.1 1888.02  4919.6 1887.52  4924.7 1887.52  4925.2 1888.02
  4928.8 1889.00  4943.0 1890.65  4957.3 1891.00  4964.9 1890.47  4985.8 1890.34
  4999.3 1891.63  5024.3 1892.04  5054.3 1893.74  5079.3 1893.68  5090.4 1890.20
  5159.3 1889.96  5171.2 1889.45  5274.3 1889.28  5320.3 1890.01  5355.5 1891.19
#Mann=3,-1,0
  4658.5    0.05       0  4919.1    0.05       0  4925.2    0.05       0
Bank Sta=4919.1,4925.2
Exp/Cntr=0.3,0.1

Type RM Length L Ch R = 1,11404,268,268,268
BEGIN DESCRIPTION:
Mapping XS 6ac2a3cd
END DESCRIPTION:
XS GIS Cut Line= 3
      1621102.57      6802107.28      1621449.78      6802405.88
      1621650.56      6802606.66
#Sta/Elev= 30
  4692.0 1899.35  4715.6 1899.76  4828.6 1897.59  4857.1 1895.79  4864.8 1894.12
  4879.0 1892.19  4893.1 1891.29  4963.5 1888.27  4971.2 1888.28  4977.8 1889.03
  4992.1 1888.31  5006.3 1888.60  5024.1 1888.13  5024.6 1887.63  5029.7 1887.63
  5030.2 1888.13  5034.9 1888.62  5070.0 1888.21  5141.3 1889.17  5147.7 1888.50
  5190.5 1888.97  5232.9 1888.72  5268.3 1889.17  5324.8 1890.88  5346.1 1890.82
  5374.3 1891.69  5381.4 1891.21  5388.5 1893.14  5402.6 1891.05  5433.9 1892.51
#Mann=3,-1,0
  4692.0    0.05       0  5024.1    0.05       0  5030.2    0.05       0
Bank Sta=5024.1,5030.2
Exp/Cntr=0.3,0.1

Type RM Length L Ch R = 1,11136,402,402,402
BEGIN DESCRIPTION:
Elm 01 88 11135.95
END DESCRIPTION:
XS GIS Cut Line= 3
      1620940.46      6802462.57      1621211.70      6802529.83
      1621665.25      6802647.02
#Sta/Elev= 30
  4717.5 1896.06  4753.1 1896.08  4835.5 1894.79  4866.4 1893.08  4876.7 1892.16
  4888.8 1889.98  4917.9 1888.00  4938.5 1887.33  4966.4 1887.25  4971.6 1886.64
  4979.8 1887.40  5001.2 1887.11  5004.5 1885.24  5005.0 1884.74  5010.2 1884.74
  5010.7 1885.24  5012.7 1886.23  5021.0 1887.18  5072.7 1886.79  5103.6 1885.78
  5165.0 1886.89  5196.6 1887.98  5320.5 1889.67  5341.2 1890.59  5361.9 1890.42
  5382.5 1891.84  5392.8 1890.74  5403.2 1890.98  5408.8 1891.79  5465.4 1892.69
#Mann=3,-1,0
  4717.5    0.05       0  5004.5    0.03       0  5010.7    0.05       0
Bank Sta=5004.5,5010.7
Exp/Cntr=0.3,0.1

Type RM Length L Ch R = 1,10734,250,250,250
BEGIN DESCRIPTION:
Mapping XS fb51b6e2
END DESCRIPTION:
XS GIS Cut Line= 3
      1620883.80      6802499.62      1620956.73      6802690.60
      1621352.53      6803280.84
#Sta/Elev= 30
  4618.5 1895.43  4702.4 1894.25  4719.2 1892.95  4743.9 1891.95  4749.3 1892.30
  4774.0 1889.04  4798.7 1888.74  4809.4 1887.50  4869.4 1884.99  4899.3 1882.55
  4941.4 1883.12  4997.3 1882.14  4997.8 1881.64  5003.0 1881.64  5003.5 1882.14
  5072.6 1883.22  5085.4 1884.61  5094.4 1884.77  5130.4 1884.90  5151.5 1883.84
  5181.0 1883.58  5187.5 1883.94  5217.1 1891.31  5295.5 1892.59  5325.5 1891.75
  5361.5 1892.23  5397.5 1893.00  5424.6 1894.59  5469.6 1894.97  5533.6 1896.70
#Mann=3,-1,0
  4618.5    0.05       0  4997.3    0.03       0  5003.5    0.05       0
Bank Sta=4997.3,5003.5
Exp/Cntr=0.3,0.1