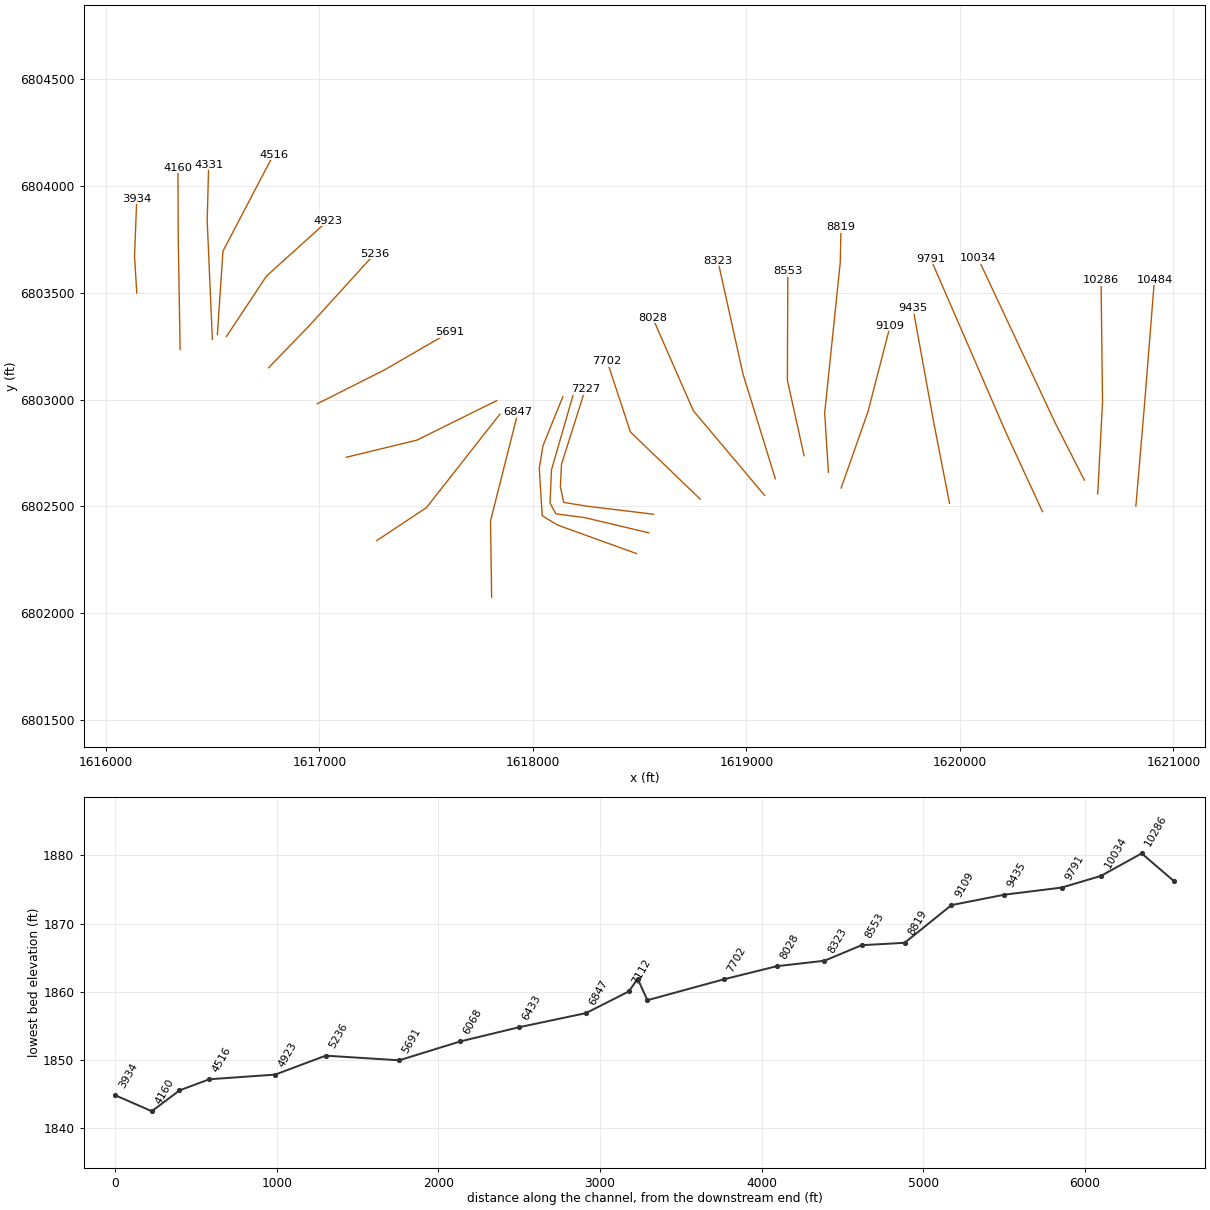
HEC-RAS study Elm 01 88.prj: Elm 01 88 Base Level Engineering

--- Elm 01 88.g01 (geometry) --- (continued)

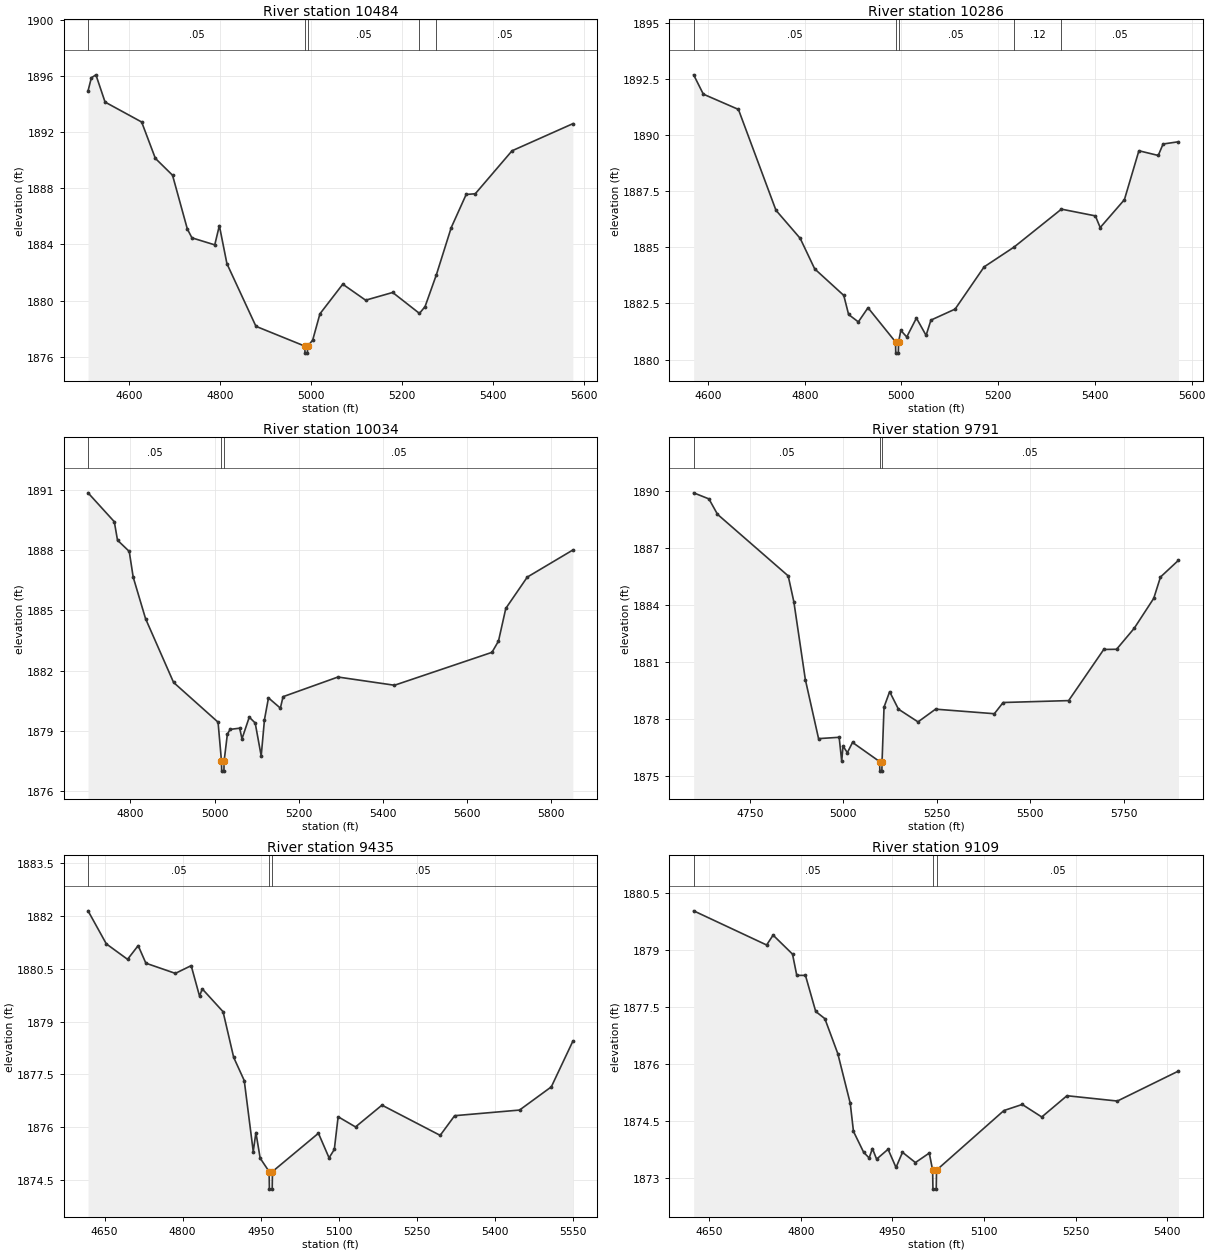
Type RM Length L Ch R = 1,10484,198,198,198
BEGIN DESCRIPTION:
Elm 01 88 10484.1
END DESCRIPTION:
XS GIS Cut Line= 3
      1620824.11      6802500.76      1620865.78      6802992.07
      1620910.91      6803561.51
#Sta/Elev= 30
  4510.6 1894.93  4517.9 1895.87  4527.9 1896.08  4548.0 1894.14  4628.3 1892.72
  4658.4 1890.13  4696.1 1888.93  4728.6 1885.10  4738.7 1884.47  4788.8 1883.97
  4798.9 1885.34  4815.5 1882.63  4879.2 1878.17  4986.4 1876.76  4986.9 1876.26
  4992.2 1876.26  4992.7 1876.76  5003.7 1877.18  5019.7 1879.06  5069.8 1881.17
  5120.0 1880.03  5179.4 1880.58  5238.1 1879.09  5250.4 1879.57  5275.3 1881.84
  5307.9 1885.20  5340.7 1887.56  5360.7 1887.61  5441.4 1890.67  5574.9 1892.60
#Mann=5,-1,0
  4510.6    0.05       0  4986.4    0.05       0  4992.7    0.05       0
  5238.1    0.12       0  5275.3    0.05       0
Bank Sta=4986.4,4992.7
Exp/Cntr=0.3,0.1

Type RM Length L Ch R = 1,10286,252,252,252
BEGIN DESCRIPTION:
Elm 01 88 10286.41
END DESCRIPTION:
XS GIS Cut Line= 3
      1620645.29      6802558.00      1620667.86      6802988.60
      1620660.91      6803559.77
#Sta/Elev= 30
  4570.4 1892.68  4590.4 1891.82  4663.0 1891.14  4740.6 1886.65  4790.7 1885.40
  4820.7 1884.04  4880.8 1882.86  4890.8 1882.01  4910.9 1881.68  4930.9 1882.31
  4987.8 1880.79  4988.3 1880.29  4993.6 1880.29  4994.1 1880.79  4998.8 1881.30
  5011.0 1881.01  5031.0 1881.85  5051.0 1881.08  5061.0 1881.76  5111.0 1882.25
  5171.0 1884.13  5232.8 1885.01  5330.8 1886.70  5401.0 1886.40  5411.0 1885.88
  5461.0 1887.12  5491.0 1889.30  5531.0 1889.09  5541.0 1889.60  5572.8 1889.70
#Mann=5,-1,0
  4570.4    0.05       0  4987.8    0.03       0  4994.1    0.05       0
  5232.8    0.12       0  5330.8    0.05       0
Bank Sta=4987.8,4994.1
Exp/Cntr=0.3,0.1

Type RM Length L Ch R = 1,10034,243,243,243
BEGIN DESCRIPTION:
Elm 01 88 10034.44
END DESCRIPTION:
XS GIS Cut Line= 3
      1620582.77      6802622.32      1620445.64      6802891.38
      1620084.53      6803662.20
#Sta/Elev= 30
  4699.1 1890.86  4761.6 1889.42  4769.2 1888.50  4797.1 1887.94  4806.5 1886.66
  4835.9 1884.59  4902.6 1881.41  5008.4 1879.43  5016.5 1877.49  5017.0 1876.99
  5022.3 1876.99  5022.8 1877.49  5030.5 1878.83  5037.0 1879.07  5059.8 1879.13
  5065.3 1878.60  5082.6 1879.68  5096.7 1879.39  5111.0 1877.75  5118.8 1879.56
  5128.3 1880.64  5156.6 1880.13  5163.0 1880.70  5293.6 1881.68  5428.0 1881.27
  5659.9 1882.91  5675.4 1883.47  5692.8 1885.10  5743.9 1886.66  5852.3 1888.01
#Mann=3,-1,0
  4699.1    0.05       0  5016.5    0.05       0  5022.8    0.05       0
Bank Sta=5016.5,5022.8
Exp/Cntr=0.3,0.1

Type RM Length L Ch R = 1,9791,356,356,356
BEGIN DESCRIPTION:
Elm 01 88 9791.4
END DESCRIPTION:
XS GIS Cut Line= 3
      1620386.62      6802474.69      1620218.21      6802839.30
      1619862.31      6803660.47
#Sta/Elev= 30
  4600.1 1889.92  4641.0 1889.60  4663.9 1888.79  4853.0 1885.55  4868.1 1884.19
  4898.8 1880.10  4934.2 1876.99  4989.3 1877.06  4996.1 1875.80  4999.6 1876.60
  5011.2 1876.25  5025.0 1876.79  5097.6 1875.78  5098.1 1875.28  5103.5 1875.28
  5104.0 1875.78  5109.3 1878.65  5124.3 1879.46  5147.8 1878.54  5200.2 1877.87
  5247.1 1878.54  5404.3 1878.30  5427.8 1878.89  5603.0 1878.99  5696.9 1881.68
  5731.2 1881.69  5778.2 1882.79  5830.6 1884.37  5848.6 1885.49  5896.7 1886.37
#Mann=3,-1,0
  4600.1    0.05       0  5097.6    0.03       0  5104.0    0.05       0
Bank Sta=5097.6,5104
Exp/Cntr=0.3,0.1

Type RM Length L Ch R = 1,9435,326,326,326
BEGIN DESCRIPTION:
Elm 01 88 9434.8
END DESCRIPTION:
XS GIS Cut Line= 3
      1619951.22      6802513.53      1619877.43      6802891.14
      1619779.89      6803428.71
#Sta/Elev= 30
  4618.3 1882.15  4653.4 1881.21  4694.2 1880.77  4714.6 1881.16  4729.4 1880.66
  4786.0 1880.37  4816.4 1880.59  4832.5 1879.72  4837.6 1879.93  4877.6 1879.28
  4898.0 1877.98  4918.3 1877.32  4935.6 1875.30  4940.7 1875.84  4948.9 1875.11
  4966.1 1874.73  4966.6 1874.23  4972.0 1874.23  4972.5 1874.73  5060.8 1875.82
  5081.2 1875.12  5091.3 1875.36  5098.6 1876.29  5132.0 1876.00  5182.8 1876.62
  5294.6 1875.76  5322.4 1876.32  5447.0 1876.48  5508.0 1877.14  5549.4 1878.44
#Mann=3,-1,0
  4618.3    0.05       0  4966.1    0.05       0  4972.5    0.05       0
Bank Sta=4966.1,4972.5
Exp/Cntr=0.3,0.1

Type RM Length L Ch R = 1,9109,290,290,290
BEGIN DESCRIPTION:
Elm 01 88 9109.14
END DESCRIPTION:
XS GIS Cut Line= 3
      1619443.41      6802585.16      1619569.27      6802943.23
      1619672.93      6803344.92
#Sta/Elev= 30
  4624.2 1880.04  4743.8 1879.14  4754.4 1879.40  4786.2 1878.90  4793.2 1878.34
  4807.4 1878.34  4824.2 1877.39  4839.2 1877.20  4860.4 1876.28  4880.8 1874.97
  4886.1 1874.23  4902.8 1873.68  4911.8 1873.53  4917.1 1873.78  4924.0 1873.50
  4942.8 1873.76  4955.8 1873.28  4966.4 1873.68  4987.6 1873.41  5010.3 1873.66
  5015.8 1873.21  5016.3 1872.71  5021.7 1872.71  5022.2 1873.21  5132.6 1874.78
  5162.6 1874.94  5194.6 1874.61  5235.9 1875.17  5318.5 1875.03  5418.6 1875.82
#Mann=3,-1,0
  4624.2    0.05       0  5015.8    0.03       0  5022.2    0.05       0
Bank Sta=5015.8,5022.2
Exp/Cntr=0.3,0.1

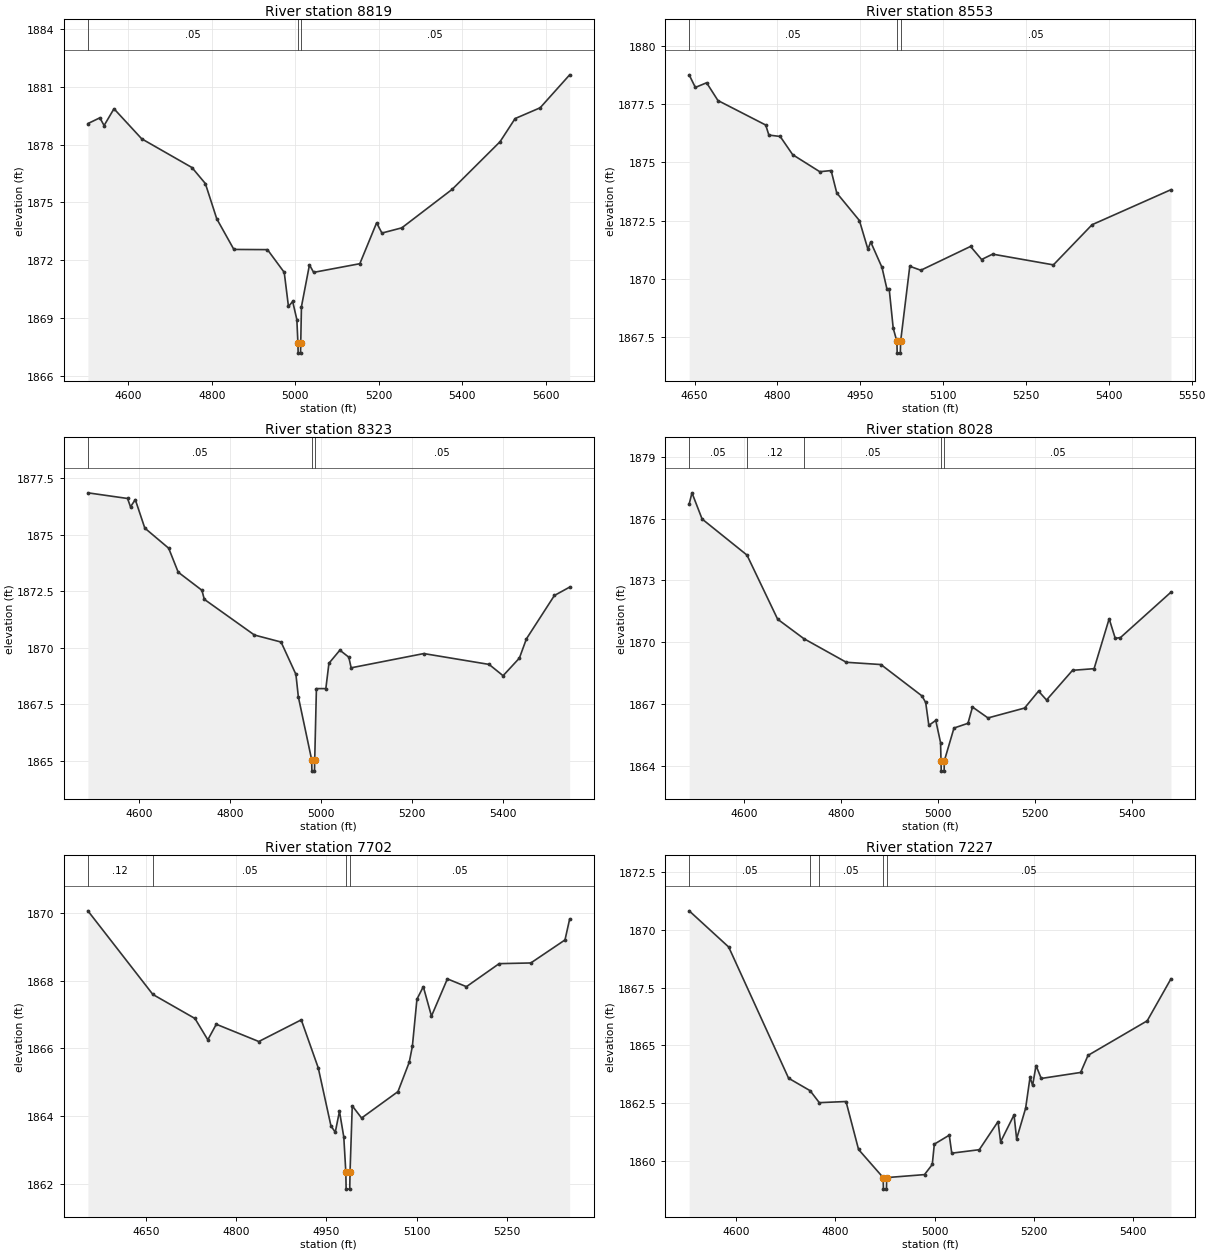
Type RM Length L Ch R = 1,8819,266,266,266
BEGIN DESCRIPTION:
Mapping XS 9dd6d940
END DESCRIPTION:
XS GIS Cut Line= 4
      1619383.81      6802659.31      1619366.45      6802937.13
      1619439.36      6803641.99      1619442.84      6803808.67
#Sta/Elev= 30
  4503.1 1879.09  4531.8 1879.39  4541.9 1878.99  4565.6 1879.86  4632.0 1878.30
  4752.3 1876.81  4784.4 1875.98  4811.7 1874.15  4852.7 1872.56  4933.1 1872.55
  4973.3 1871.37  4983.4 1869.60  4993.5 1869.86  5003.5 1868.92  5006.1 1867.68
  5006.6 1867.18  5012.3 1867.18  5012.8 1867.68  5014.5 1869.59  5033.7 1871.76
  5043.7 1871.37  5154.3 1871.82  5194.5 1873.94  5207.2 1873.41  5254.8 1873.68
  5375.5 1875.68  5490.1 1878.15  5526.1 1879.35  5586.1 1879.91  5656.8 1881.62
#Mann=3,-1,0
  4503.1    0.05       0  5006.1    0.05       0  5012.8    0.05       0
Bank Sta=5006.1,5012.8
Exp/Cntr=0.3,0.1

Type RM Length L Ch R = 1,8553,230,230,230
BEGIN DESCRIPTION:
Elm 01 88 8553.22
END DESCRIPTION:
XS GIS Cut Line= 3
      1619269.79      6802737.10      1619191.67      6803090.80
      1619193.84      6803600.77
#Sta/Elev= 30
  4640.3 1878.75  4651.5 1878.21  4671.9 1878.41  4692.4 1877.65  4778.9 1876.60
  4784.6 1876.17  4805.1 1876.11  4827.7 1875.33  4876.8 1874.60  4897.3 1874.65
  4907.5 1873.69  4948.5 1872.51  4963.9 1871.28  4969.0 1871.59  4989.4 1870.50
  4998.5 1869.56  5002.5 1869.56  5009.7 1867.90  5016.4 1867.33  5016.9 1866.83
  5022.6 1866.83  5023.1 1867.33  5039.7 1870.55  5059.7 1870.38  5149.7 1871.40
  5169.7 1870.84  5189.7 1871.07  5299.7 1870.61  5369.7 1872.33  5512.5 1873.83
#Mann=3,-1,0
  4640.3    0.05       0  5016.4    0.05       0  5023.1    0.05       0
Bank Sta=5016.4,5023.1
Exp/Cntr=0.3,0.1

Type RM Length L Ch R = 1,8323,295,295,295
BEGIN DESCRIPTION:
Elm 01 88 8323.29
END DESCRIPTION:
XS GIS Cut Line= 3
      1619135.26      6802628.52      1618983.34      6803121.18
      1618866.14      6803650.71
#Sta/Elev= 30
  4488.0 1876.86  4575.1 1876.61  4581.6 1876.24  4592.1 1876.56  4613.0 1875.30
  4665.4 1874.41  4686.3 1873.35  4738.4 1872.55  4743.6 1872.15  4853.7 1870.57
  4912.2 1870.26  4944.8 1868.83  4950.1 1867.84  4979.4 1865.05  4979.9 1864.55
  4985.6 1864.55  4986.1 1865.05  4989.8 1868.20  5010.5 1868.20  5017.3 1869.32
  5041.3 1869.90  5060.9 1869.59  5066.1 1869.12  5225.6 1869.75  5369.0 1869.27
  5399.7 1868.77  5435.5 1869.55  5450.9 1870.40  5512.4 1872.32  5545.9 1872.69
#Mann=3,-1,0
  4488.0    0.05       0  4979.4    0.05       0  4986.1    0.05       0
Bank Sta=4979.4,4986.1
Exp/Cntr=0.3,0.1

Type RM Length L Ch R = 1,8028,326,326,326
BEGIN DESCRIPTION:
Elm 01 88 8028.11
END DESCRIPTION:
XS GIS Cut Line= 3
      1619085.35      6802550.42      1618751.13      6802947.57
      1618560.33      6803383.37
#Sta/Elev= 30
  4486.5 1876.70  4492.3 1877.25  4513.2 1875.98  4605.9 1874.23  4669.2 1871.12
  4723.1 1870.18  4811.0 1869.03  4882.5 1868.92  4967.1 1867.40  4974.9 1867.08
  4981.4 1865.97  4995.7 1866.21  5005.6 1865.13  5006.5 1864.25  5007.0 1863.75
  5012.9 1863.75  5013.4 1864.25  5033.3 1865.84  5062.2 1866.07  5071.5 1866.86
  5103.5 1866.33  5179.1 1866.81  5207.9 1867.63  5224.4 1867.20  5278.1 1868.64
  5322.6 1868.72  5353.7 1871.14  5366.3 1870.19  5377.1 1870.23  5481.3 1872.43
#Mann=5,-1,0
  4486.5    0.05       0  4605.9    0.12       0  4723.1    0.05       0
  5006.5    0.05       0  5013.4    0.05       0
Bank Sta=5006.5,5013.4
Exp/Cntr=0.3,0.1

Type RM Length L Ch R = 1,7702,475,475,475
BEGIN DESCRIPTION:
Elm 01 88 7702.28
END DESCRIPTION:
XS GIS Cut Line= 3
      1618782.98      6802533.68      1618456.60      6802847.91
      1618347.24      6803179.48
#Sta/Elev= 30
  4552.7 1870.06  4660.9 1867.59  4731.0 1866.88  4752.4 1866.25  4766.5 1866.71
  4837.3 1866.20  4908.0 1866.84  4936.3 1865.42  4957.4 1863.71  4964.6 1863.52
  4971.6 1864.14  4978.8 1863.38  4982.2 1862.34  4982.7 1861.84  4988.7 1861.84
  4989.2 1862.34  4992.9 1864.30  5008.4 1863.94  5069.0 1864.72  5087.8 1865.59
  5093.0 1866.06  5100.6 1867.45  5111.2 1867.82  5124.8 1866.95  5151.3 1868.05
  5183.0 1867.82  5237.5 1868.50  5290.2 1868.52  5347.1 1869.20  5354.9 1869.82
#Mann=4,-1,0
  4552.7    0.12       0  4660.9    0.05       0  4982.2    0.05       0
  4989.2    0.05       0
Bank Sta=4982.2,4989.2
Exp/Cntr=0.3,0.1

Type RM Length L Ch R = 1,7227,60,60,60
BEGIN DESCRIPTION:
Elm 01 88 7227.41
END DESCRIPTION:
XS GIS Cut Line= 6
      1618564.25      6802462.50      1618250.00      6802500.69
      1618144.10      6802518.05      1618128.47      6802590.97
      1618133.68      6802696.87      1618244.81      6803047.61
#Sta/Elev= 30
  4504.8 1870.83  4584.6 1869.26  4705.5 1863.57  4748.9 1863.03  4767.5 1862.51
  4821.4 1862.56  4846.7 1860.48  4896.4 1859.26  4896.9 1858.76  4903.0 1858.76
  4903.5 1859.26  4979.8 1859.39  4995.5 1859.83  4999.6 1860.71  5029.8 1861.10
  5034.8 1860.32  5090.4 1860.47  5128.2 1861.69  5133.4 1860.81  5160.5 1861.98
  5165.7 1860.94  5183.9 1862.27  5192.8 1863.61  5198.0 1863.26  5204.9 1864.12
  5215.4 1863.56  5294.9 1863.82  5309.8 1864.56  5429.3 1866.06  5477.2 1867.88
#Mann=5,-1,0
  4504.8    0.05       0  4748.9    0.12       0  4767.5    0.05       0
  4896.4    0.05       0  4903.5    0.05       0
Bank Sta=4896.4,4903.5
Exp/Cntr=0.3,0.1

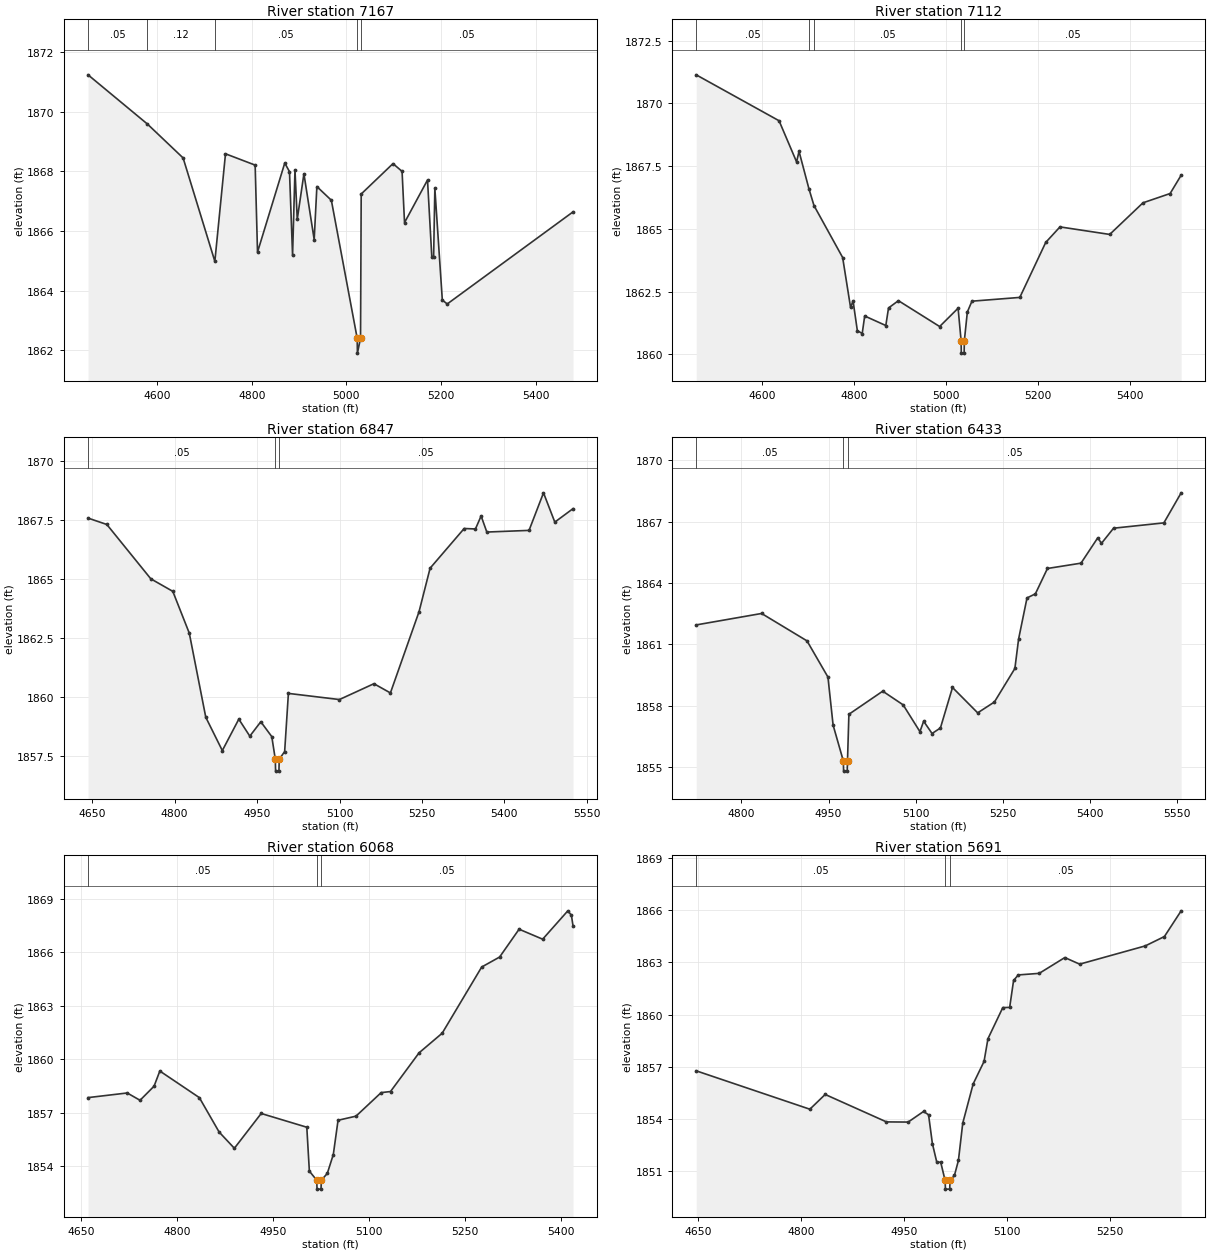
Type RM Length L Ch R = 1,7167,55,55,55
BEGIN DESCRIPTION:
Elm 01 88 7167.26
END DESCRIPTION:
XS GIS Cut Line= 6
      1618541.64      6802375.70      1618241.32      6802446.87
      1618107.64      6802464.23      1618079.86      6802514.58
      1618086.81      6802670.83      1618188.96      6803024.02
#Sta/Elev= 30
  4453.8 1871.24  4579.2 1869.59  4654.8 1868.45  4721.9 1864.98  4744.4 1868.59
  4807.1 1868.21  4812.1 1865.29  4869.7 1868.28  4879.7 1867.99  4886.2 1865.18
  4891.3 1868.05  4896.1 1866.39  4910.2 1867.92  4931.9 1865.71  4937.6 1867.49
  4968.2 1867.03  5022.8 1862.40  5023.3 1861.90  5029.9 1862.40  5031.3 1867.24
  5098.5 1868.26  5117.7 1868.00  5122.9 1866.28  5171.5 1867.71  5180.6 1865.12
  5184.4 1865.12  5187.0 1867.43  5202.8 1863.68  5213.2 1863.55  5479.1 1866.64
#Mann=5,-1,0
  4453.8    0.05       0  4579.2    0.12       0  4721.9    0.05       0
  5022.8    0.05       0  5029.9    0.05       0
Bank Sta=5022.8,5029.9
Exp/Cntr=0.3,0.1

Type RM Length L Ch R = 1,7112,265,265,265
BEGIN DESCRIPTION:
Elm 01 88 7112.15
END DESCRIPTION:
XS GIS Cut Line= 6
      1618484.34      6802278.48      1618114.59      6802412.15
      1618043.40      6802455.55      1618029.52      6802677.78
      1618046.88      6802783.68      1618139.98      6803012.98
#Sta/Elev= 30
  4457.0 1871.14  4637.1 1869.31  4675.2 1867.67  4680.5 1868.09  4702.0 1866.60
  4713.0 1865.93  4775.3 1863.86  4792.5 1861.87  4797.9 1862.13  4807.2 1860.95
  4817.8 1860.83  4823.2 1861.53  4869.1 1861.15  4875.0 1861.85  4896.5 1862.14
  4986.1 1861.11  5026.2 1861.84  5032.7 1860.55  5033.2 1860.05  5039.3 1860.05
  5039.8 1860.55  5046.3 1861.69  5056.3 1862.12  5160.3 1862.27  5216.6 1864.46
  5247.6 1865.08  5355.7 1864.78  5428.0 1866.04  5487.0 1866.41  5511.0 1867.14
#Mann=5,-1,0
  4457.0    0.05       0  4702.0    0.12       0  4713.0    0.05       0
  5032.7    0.05       0  5039.8    0.05       0
Bank Sta=5032.7,5039.8
Exp/Cntr=0.3,0.1

Type RM Length L Ch R = 1,6847,414,414,414
BEGIN DESCRIPTION:
Elm 01 88 6847.18
END DESCRIPTION:
XS GIS Cut Line= 3
      1617806.45      6802073.77      1617801.24      6802431.39
      1617929.71      6802940.06
#Sta/Elev= 30
  4642.5 1867.58  4676.7 1867.31  4756.7 1865.01  4796.7 1864.48  4826.7 1862.71
  4856.7 1859.15  4886.8 1857.74  4916.8 1859.07  4936.8 1858.35  4956.8 1858.96
  4976.8 1858.33  4983.2 1857.37  4983.7 1856.87  4989.8 1856.87  4990.3 1857.37
  5000.2 1857.70  5007.0 1860.16  5099.8 1859.90  5162.6 1860.57  5192.6 1860.18
  5244.7 1863.62  5264.8 1865.46  5326.8 1867.14  5347.3 1867.12  5357.6 1867.67
  5368.0 1866.99  5444.8 1867.06  5471.1 1868.65  5491.7 1867.41  5524.8 1867.98
#Mann=3,-1,0
  4642.5    0.05       0  4983.2    0.05       0  4990.3    0.05       0
Bank Sta=4983.2,4990.3
Exp/Cntr=0.3,0.1

Type RM Length L Ch R = 1,6433,365,365,365
BEGIN DESCRIPTION:
Elm 01 88 6433.32
END DESCRIPTION:
XS GIS Cut Line= 3
      1617268.46      6802339.05      1617501.07      6802493.54
      1617844.80      6802931.02
#Sta/Elev= 30
  4722.0 1861.95  4834.7 1862.51  4912.9 1861.17  4949.0 1859.40  4957.9 1857.05
  4975.5 1855.30  4976.0 1854.80  4982.2 1854.80  4982.7 1855.30  4985.1 1857.58
  5043.4 1858.71  5078.6 1858.04  5107.5 1856.73  5113.9 1857.24  5128.4 1856.64
  5142.8 1856.91  5163.6 1858.89  5207.0 1857.65  5235.8 1858.18  5271.1 1859.82
  5277.5 1861.26  5292.0 1863.27  5306.4 1863.47  5327.2 1864.71  5385.0 1864.97
  5413.9 1866.21  5420.3 1865.94  5441.1 1866.68  5527.8 1866.94  5557.6 1868.41
#Mann=3,-1,0
  4722.0    0.05       0  4975.5    0.05       0  4982.7    0.05       0
Bank Sta=4975.5,4982.7
Exp/Cntr=0.3,0.1

Type RM Length L Ch R = 1,6068,377,377,377
BEGIN DESCRIPTION:
Elm 01 88 6068.47
END DESCRIPTION:
XS GIS Cut Line= 3
      1617126.08      6802729.65      1617455.93      6802809.51
      1617830.42      6802995.02
#Sta/Elev= 30
  4661.4 1857.84  4722.6 1858.10  4742.6 1857.69  4764.5 1858.48  4773.5 1859.33
  4835.2 1857.84  4866.1 1855.91  4889.9 1855.00  4931.8 1856.95  5003.0 1856.18
  5007.0 1853.72  5018.5 1853.21  5019.0 1852.71  5025.2 1852.71  5025.7 1853.21
  5035.0 1853.59  5044.4 1854.65  5051.8 1856.57  5079.8 1856.80  5119.1 1858.12
  5133.7 1858.18  5178.3 1860.35  5214.4 1861.45  5276.1 1865.16  5304.1 1865.72
  5334.5 1867.28  5371.3 1866.72  5410.6 1868.31  5416.2 1868.06  5418.7 1867.47
#Mann=3,-1,0
  4661.4    0.05       0  5018.5    0.05       0  5025.7    0.05       0
Bank Sta=5018.5,5025.7
Exp/Cntr=0.3,0.1

Type RM Length L Ch R = 1,5691,455,455,455
BEGIN DESCRIPTION:
Elm 01 88 5690.54
END DESCRIPTION:
XS GIS Cut Line= 3
      1616989.45      6802979.93      1617304.51      6803138.76
      1617610.27      6803315.71
#Sta/Elev= 30
  4647.6 1856.76  4813.1 1854.55  4835.4 1855.40  4924.6 1853.82  4956.2 1853.81
  4978.6 1854.42  4985.9 1854.23  4991.5 1852.57  4997.9 1851.50  5003.6 1851.50
  5010.0 1850.45  5010.5 1849.95  5016.7 1849.95  5017.2 1850.45  5023.6 1850.74
  5029.4 1851.60  5035.7 1853.75  5050.9 1856.01  5066.7 1857.30  5072.4 1858.61
  5094.0 1860.40  5104.0 1860.41  5109.7 1861.96  5116.5 1862.28  5147.0 1862.37
  5184.3 1863.28  5205.9 1862.90  5301.4 1863.95  5329.3 1864.49  5353.7 1865.97
#Mann=3,-1,0
  4647.6    0.05       0  5010.0    0.05       0  5017.2    0.05       0
Bank Sta=5010,5017.2
Exp/Cntr=0.3,0.1

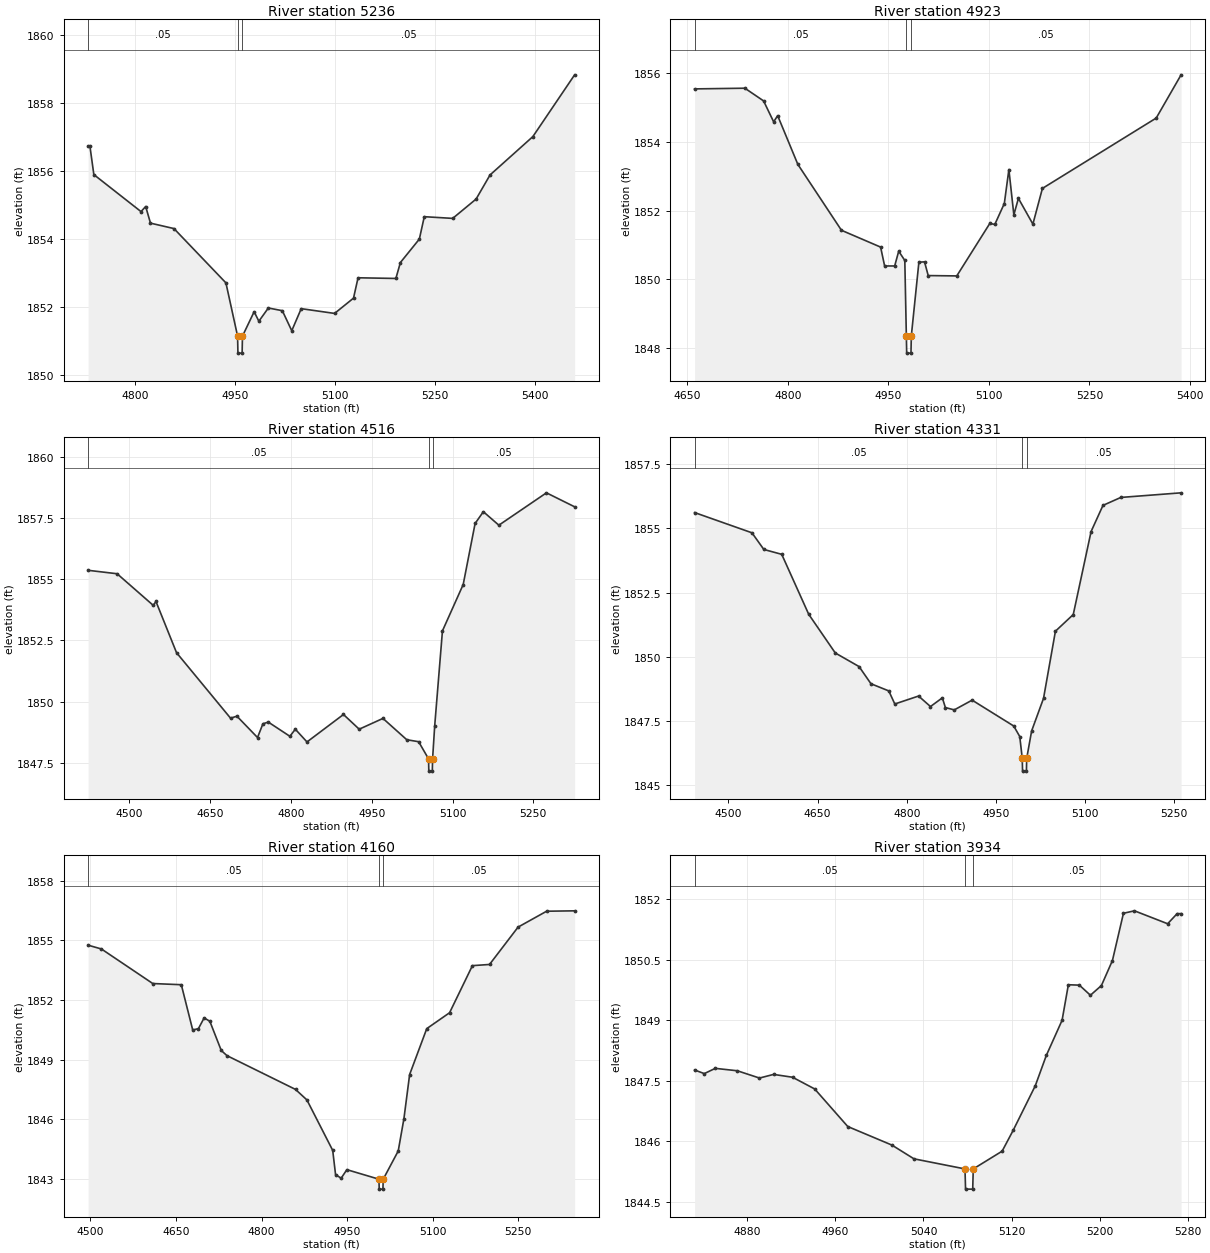
Type RM Length L Ch R = 1,5236,313,313,313
BEGIN DESCRIPTION:
Elm 01 88 5235.87
END DESCRIPTION:
XS GIS Cut Line= 3
      1616761.87      6803149.08      1616950.67      6803344.38
      1617258.81      6803682.91
#Sta/Elev= 30
  4730.1 1856.73  4732.8 1856.73  4738.7 1855.89  4809.4 1854.80  4816.4 1854.95
  4823.6 1854.46  4858.8 1854.30  4936.7 1852.70  4954.2 1851.13  4954.7 1850.63
  4961.0 1850.63  4961.5 1851.13  4979.0 1851.85  4986.1 1851.57  5000.3 1851.96
  5021.3 1851.88  5035.4 1851.29  5049.6 1851.94  5099.6 1851.80  5128.0 1852.25
  5134.8 1852.85  5191.5 1852.83  5198.3 1853.30  5226.7 1853.99  5234.1 1854.65
  5276.7 1854.60  5311.8 1855.17  5332.7 1855.88  5396.9 1857.01  5459.5 1858.83
#Mann=3,-1,0
  4730.1    0.05       0  4954.2    0.03       0  4961.5    0.05       0
Bank Sta=4954.2,4961.5
Exp/Cntr=0.3,0.1

Type RM Length L Ch R = 1,4923,407,407,407
BEGIN DESCRIPTION:
Elm 01 88 4922.84
END DESCRIPTION:
XS GIS Cut Line= 3
      1616564.34      6803295.46      1616751.85      6803578.47
      1617038.34      6803837.17
#Sta/Elev= 30
  4661.1 1855.55  4736.1 1855.57  4764.0 1855.20  4779.0 1854.59  4785.0 1854.77
  4815.1 1853.35  4880.1 1851.43  4938.5 1850.94  4944.5 1850.39  4959.5 1850.39
  4965.5 1850.82  4974.6 1850.55  4976.9 1848.35  4977.4 1847.85  4983.8 1847.85
  4984.3 1848.35  4995.6 1850.50  5004.0 1850.51  5009.5 1850.11  5052.1 1850.10
  5101.4 1851.63  5108.8 1851.60  5123.0 1852.21  5129.8 1853.20  5137.2 1851.88
  5144.0 1852.36  5165.6 1851.61  5179.8 1852.65  5349.5 1854.70  5386.6 1855.96
#Mann=3,-1,0
  4661.1    0.05       0  4976.9    0.03       0  4984.3    0.05       0
Bank Sta=4976.9,4984.3
Exp/Cntr=0.3,0.1

Type RM Length L Ch R = 1,4516,185,185,185
BEGIN DESCRIPTION:
Mapping XS 16bae4d2
END DESCRIPTION:
XS GIS Cut Line= 3
      1616521.83      6803304.31      1616547.87      6803694.94
      1616784.87      6804148.11
#Sta/Elev= 30
  4423.7 1855.36  4477.5 1855.22  4544.6 1853.93  4549.6 1854.09  4587.8 1852.00
  4688.0 1849.33  4699.9 1849.41  4738.1 1848.54  4748.1 1849.10  4758.1 1849.17
  4798.2 1848.59  4808.2 1848.88  4829.9 1848.36  4897.6 1849.48  4926.8 1848.88
  4970.9 1849.32  5015.1 1848.45  5037.1 1848.37  5055.5 1847.67  5056.0 1847.17
  5062.5 1847.17  5063.0 1847.67  5066.9 1849.01  5081.3 1852.89  5119.8 1854.78
  5141.9 1857.27  5157.2 1857.75  5186.0 1857.20  5274.3 1858.52  5326.6 1857.95
#Mann=3,-1,0
  4423.7    0.05       0  5055.5    0.03       0  5063.0    0.05       0
Bank Sta=5055.5,5063
Exp/Cntr=0.3,0.1

Type RM Length L Ch R = 1,4331,171,171,171
BEGIN DESCRIPTION:
Elm 01 88 4331.45
END DESCRIPTION:
XS GIS Cut Line= 3
      1616498.38      6803281.56      1616474.08      6803838.89
      1616481.02      6804099.34
#Sta/Elev= 30
  4443.1 1855.62  4539.6 1854.83  4559.6 1854.18  4589.7 1853.99  4635.1 1851.65
  4679.8 1850.14  4719.8 1849.61  4739.8 1848.94  4769.8 1848.66  4779.9 1848.15
  4819.9 1848.46  4839.9 1848.05  4859.9 1848.39  4865.0 1848.01  4880.0 1847.92
  4910.0 1848.30  4980.0 1847.29  4990.1 1846.88  4994.3 1846.03  4994.8 1845.53
  5001.3 1845.53  5001.8 1846.03  5010.1 1847.10  5030.1 1848.37  5050.1 1850.99
  5080.1 1851.64  5110.1 1854.88  5130.1 1855.90  5160.1 1856.21  5261.5 1856.39
#Mann=3,-1,0
  4443.1    0.05       0  4994.3    0.05       0  5001.8    0.05       0
Bank Sta=4994.3,5001.8
Exp/Cntr=0.3,0.1

Type RM Length L Ch R = 1,4160,226,226,226
BEGIN DESCRIPTION:
Elm 01 88 4159.59
END DESCRIPTION:
XS GIS Cut Line= 3
      1616347.34      6803234.69      1616338.66      6803741.66
      1616336.92      6804087.11
#Sta/Elev= 30
  4496.1 1854.76  4519.4 1854.57  4609.4 1852.83  4659.4 1852.77  4679.4 1850.49
  4689.4 1850.56  4699.4 1851.10  4709.4 1850.93  4729.4 1849.46  4739.4 1849.20
  4859.5 1847.50  4879.5 1846.97  4924.7 1844.43  4929.7 1843.21  4939.5 1843.03
  4949.5 1843.46  5005.7 1842.98  5006.2 1842.48  5012.7 1842.48  5013.2 1842.98
  5039.5 1844.40  5049.5 1846.03  5059.5 1848.25  5089.5 1850.56  5129.5 1851.36
  5169.5 1853.73  5199.5 1853.79  5249.5 1855.67  5299.5 1856.47  5348.6 1856.49
#Mann=3,-1,0
  4496.1    0.05       0  5005.7    0.05       0  5013.2    0.05       0
Bank Sta=5005.7,5013.2
Exp/Cntr=0.3,0.1

Type RM Length L Ch R = 1,3934,307,307,307
BEGIN DESCRIPTION:
Elm 01 88 3933.63
END DESCRIPTION:
XS GIS Cut Line= 3
      1616144.21      6803499.25      1616133.79      6803671.14
      1616144.21      6803940.23
#Sta/Elev= 30
  4832.3 1847.77  4841.1 1847.68  4851.1 1847.81  4871.1 1847.75  4891.2 1847.57
  4904.0 1847.66  4921.2 1847.59  4941.3 1847.30  4971.3 1846.37  5011.4 1845.91
  5031.4 1845.57  5077.7 1845.32  5078.2 1844.82  5084.7 1844.82  5085.2 1845.32
  5111.4 1845.76  5121.5 1846.28  5141.5 1847.38  5151.5 1848.13  5165.8 1849.00
  5171.5 1849.88  5181.5 1849.87  5191.5 1849.62  5201.5 1849.86  5211.5 1850.48
  5221.5 1851.65  5231.5 1851.71  5261.6 1851.39  5270.2 1851.64  5273.8 1851.64
#Mann=3,-1,0
  4832.3    0.05       0  5077.7    0.03       0  5085.2    0.05       0
Bank Sta=5077.7,5085.2
Exp/Cntr=0.3,0.1