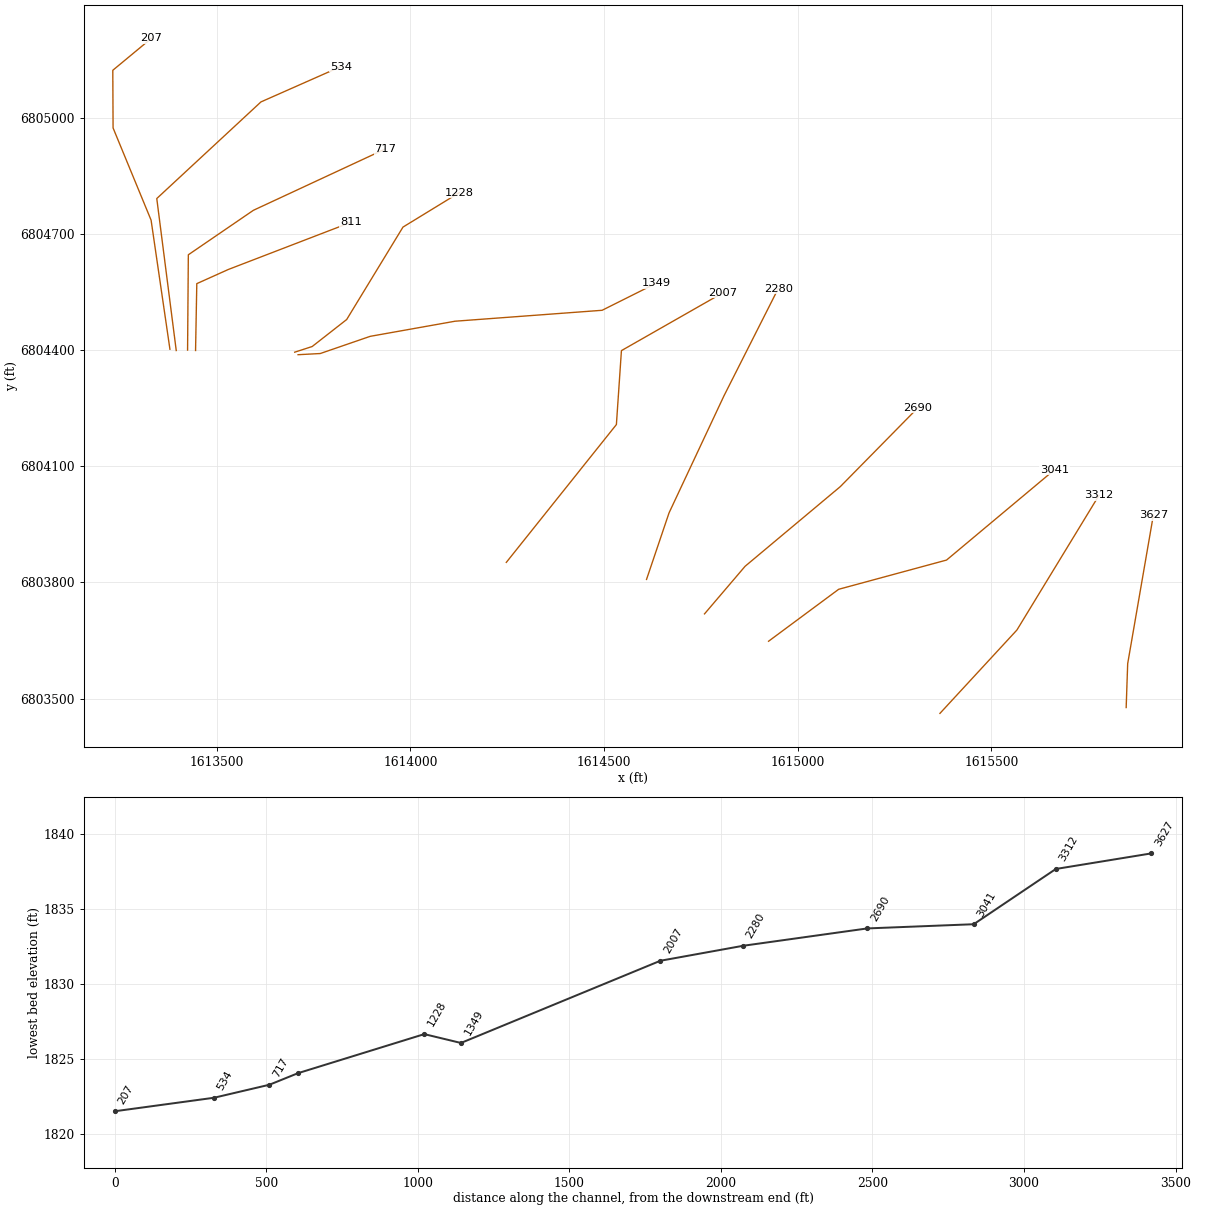
HEC-RAS study Elm 01 88.prj: Elm 01 88 Base Level Engineering

--- Elm 01 88.g01 (geometry) --- (continued)

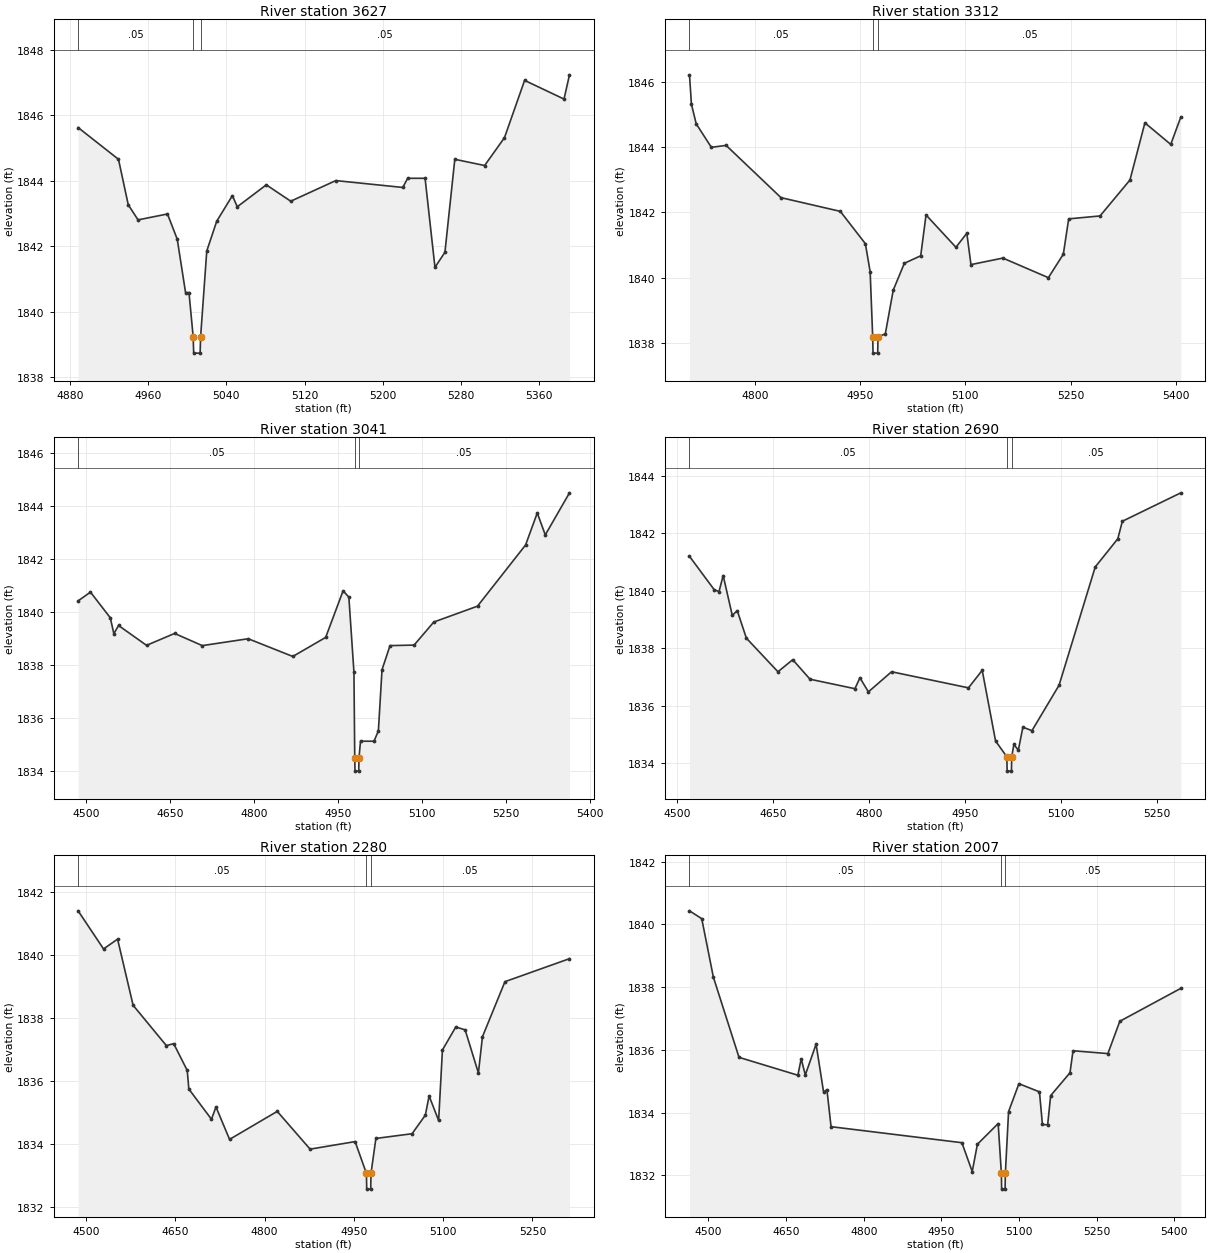
Type RM Length L Ch R = 1,3627,315,315,315
BEGIN DESCRIPTION:
Elm 01 88 3627.02
END DESCRIPTION:
XS GIS Cut Line= 3
      1615848.40      6803476.70      1615852.31      6803589.99
      1615918.62      6803973.54
#Sta/Elev= 30
  4888.4 1845.62  4929.7 1844.65  4939.7 1843.26  4949.7 1842.80  4979.8 1842.98
  4989.8 1842.21  4998.3 1840.58  5001.8 1840.58  5006.1 1839.23  5006.6 1838.73
  5013.2 1838.73  5013.7 1839.23  5020.0 1841.85  5030.2 1842.76  5046.2 1843.54
  5051.2 1843.20  5080.9 1843.87  5105.9 1843.37  5152.0 1844.00  5220.5 1843.79
  5225.5 1844.07  5243.3 1844.07  5253.4 1841.35  5263.6 1841.81  5273.7 1844.65
  5304.2 1844.46  5324.5 1845.31  5345.1 1847.06  5385.4 1846.49  5391.0 1847.23
#Mann=3,-1,0
  4888.4    0.05       0  5006.1    0.03       0  5013.7    0.05       0
Bank Sta=5006.1,5013.7
Exp/Cntr=0.3,0.1

Type RM Length L Ch R = 1,3312,271,271,271
BEGIN DESCRIPTION:
Elm 01 88 3311.52
END DESCRIPTION:
XS GIS Cut Line= 3
      1615367.44      6803461.63      1615566.20      6803676.88
      1615778.02      6804024.44
#Sta/Elev= 30
  4706.9 1846.21  4709.7 1845.31  4716.5 1844.71  4738.1 1843.99  4759.1 1844.05
  4837.3 1842.45  4921.8 1842.03  4957.5 1841.04  4964.3 1840.18  4967.9 1838.19
  4968.4 1837.69  4975.0 1837.69  4975.5 1838.19  4985.9 1838.28  4997.2 1839.62
  5013.0 1840.44  5036.3 1840.67  5043.9 1841.92  5086.5 1840.93  5102.0 1841.36
  5107.9 1840.40  5153.4 1840.60  5218.2 1840.00  5239.5 1840.72  5247.1 1841.80
  5291.8 1841.89  5334.4 1842.99  5355.7 1844.74  5392.5 1844.08  5406.9 1844.92
#Mann=3,-1,0
  4706.9    0.05       0  4967.9    0.03       0  4975.5    0.05       0
Bank Sta=4967.9,4975.5
Exp/Cntr=0.3,0.1

Type RM Length L Ch R = 1,3041,351,351,351
BEGIN DESCRIPTION:
Elm 01 88 3040.68
END DESCRIPTION:
XS GIS Cut Line= 4
      1614924.84      6803647.95      1615105.87      6803782.09
      1615384.51      6803857.61      1615663.18      6804090.70
#Sta/Elev= 30
  4485.9 1840.43  4508.0 1840.76  4543.4 1839.79  4549.7 1839.19  4558.1 1839.50
  4608.1 1838.75  4658.2 1839.20  4707.6 1838.74  4789.6 1839.00  4869.2 1838.33
  4927.9 1839.05  4959.0 1840.81  4969.3 1840.57  4978.4 1837.73  4979.8 1834.50
  4980.3 1834.00  4986.9 1834.00  4987.4 1834.50  4990.1 1835.13  5014.2 1835.13
  5022.0 1835.52  5028.5 1837.83  5042.8 1838.74  5085.8 1838.76  5120.9 1839.63
  5199.0 1840.23  5284.8 1842.54  5305.7 1843.75  5320.0 1842.92  5363.2 1844.51
#Mann=3,-1,0
  4485.9    0.05       0  4979.8    0.05       0  4987.4    0.05       0
Bank Sta=4979.8,4987.4
Exp/Cntr=0.3,0.1

Type RM Length L Ch R = 1,2690,410,410,410
BEGIN DESCRIPTION:
Elm 01 88 2689.97
END DESCRIPTION:
XS GIS Cut Line= 4
      1614759.41      6803718.60      1614864.20      6803841.51
      1615110.21      6804047.35      1615311.04      6804251.42
#Sta/Elev= 30
  4519.2 1841.20  4557.8 1840.04  4565.4 1839.97  4571.9 1840.53  4586.2 1839.14
  4593.9 1839.31  4608.2 1838.35  4657.6 1837.18  4680.7 1837.60  4707.8 1836.92
  4778.0 1836.59  4785.8 1836.97  4799.1 1836.48  4835.3 1837.18  4955.6 1836.62
  4977.1 1837.23  4998.0 1834.77  5015.6 1834.22  5016.1 1833.72  5022.8 1833.72
  5023.3 1834.22  5026.6 1834.65  5033.6 1834.45  5040.7 1835.25  5054.9 1835.13
  5097.3 1836.71  5153.9 1840.83  5189.2 1841.81  5196.3 1842.42  5287.8 1843.41
#Mann=3,-1,0
  4519.2    0.05       0  5015.6    0.05       0  5023.3    0.05       0
Bank Sta=5015.6,5023.3
Exp/Cntr=0.3,0.1

Type RM Length L Ch R = 1,2280,273,273,273
BEGIN DESCRIPTION:
Elm 01 88 2280.37
END DESCRIPTION:
XS GIS Cut Line= 4
      1614609.67      6803807.60      1614667.76      6803979.36
      1614809.64      6804281.73      1614949.61      6804558.41
#Sta/Elev= 30
  4486.9 1841.40  4529.6 1840.19  4553.2 1840.50  4579.3 1838.40  4635.1 1837.12
  4647.5 1837.18  4670.2 1836.33  4672.9 1835.74  4710.9 1834.78  4718.5 1835.17
  4741.3 1834.14  4821.4 1835.03  4876.6 1833.83  4952.2 1834.07  4971.2 1833.06
  4971.7 1832.56  4978.4 1832.56  4978.9 1833.06  4987.1 1834.17  5047.9 1834.32
  5070.2 1834.91  5076.5 1835.52  5092.5 1834.74  5098.9 1836.98  5121.3 1837.71
  5137.0 1837.62  5159.3 1836.25  5166.1 1837.40  5203.9 1839.15  5312.3 1839.88
#Mann=3,-1,0
  4486.9    0.05       0  4971.2    0.03       0  4978.9    0.05       0
Bank Sta=4971.2,4978.9
Exp/Cntr=0.3,0.1

Type RM Length L Ch R = 1,2007,658,658,658
BEGIN DESCRIPTION:
Mapping XS 3a00165e
END DESCRIPTION:
XS GIS Cut Line= 4
      1614247.51      6803851.61      1614531.81      6804207.53
      1614544.83      6804398.50      1614807.40      6804548.23
#Sta/Elev= 30
  4463.4 1840.43  4487.1 1840.18  4509.5 1838.32  4559.1 1835.76  4672.8 1835.19
  4679.2 1835.71  4687.2 1835.20  4708.0 1836.18  4722.5 1834.65  4728.9 1834.73
  4736.9 1833.55  4989.6 1833.04  5009.6 1832.12  5019.6 1832.99  5059.7 1833.65
  5065.9 1832.06  5066.4 1831.56  5073.1 1831.56  5073.6 1832.06  5079.8 1834.03
  5099.8 1834.92  5139.5 1834.66  5145.2 1833.62  5155.3 1833.61  5161.1 1834.54
  5198.5 1835.27  5204.3 1835.97  5271.7 1835.88  5294.7 1836.91  5412.6 1837.96
#Mann=3,-1,0
  4463.4    0.05       0  5065.9    0.03       0  5073.6    0.05       0
Bank Sta=5065.9,5073.6
Exp/Cntr=0.3,0.1

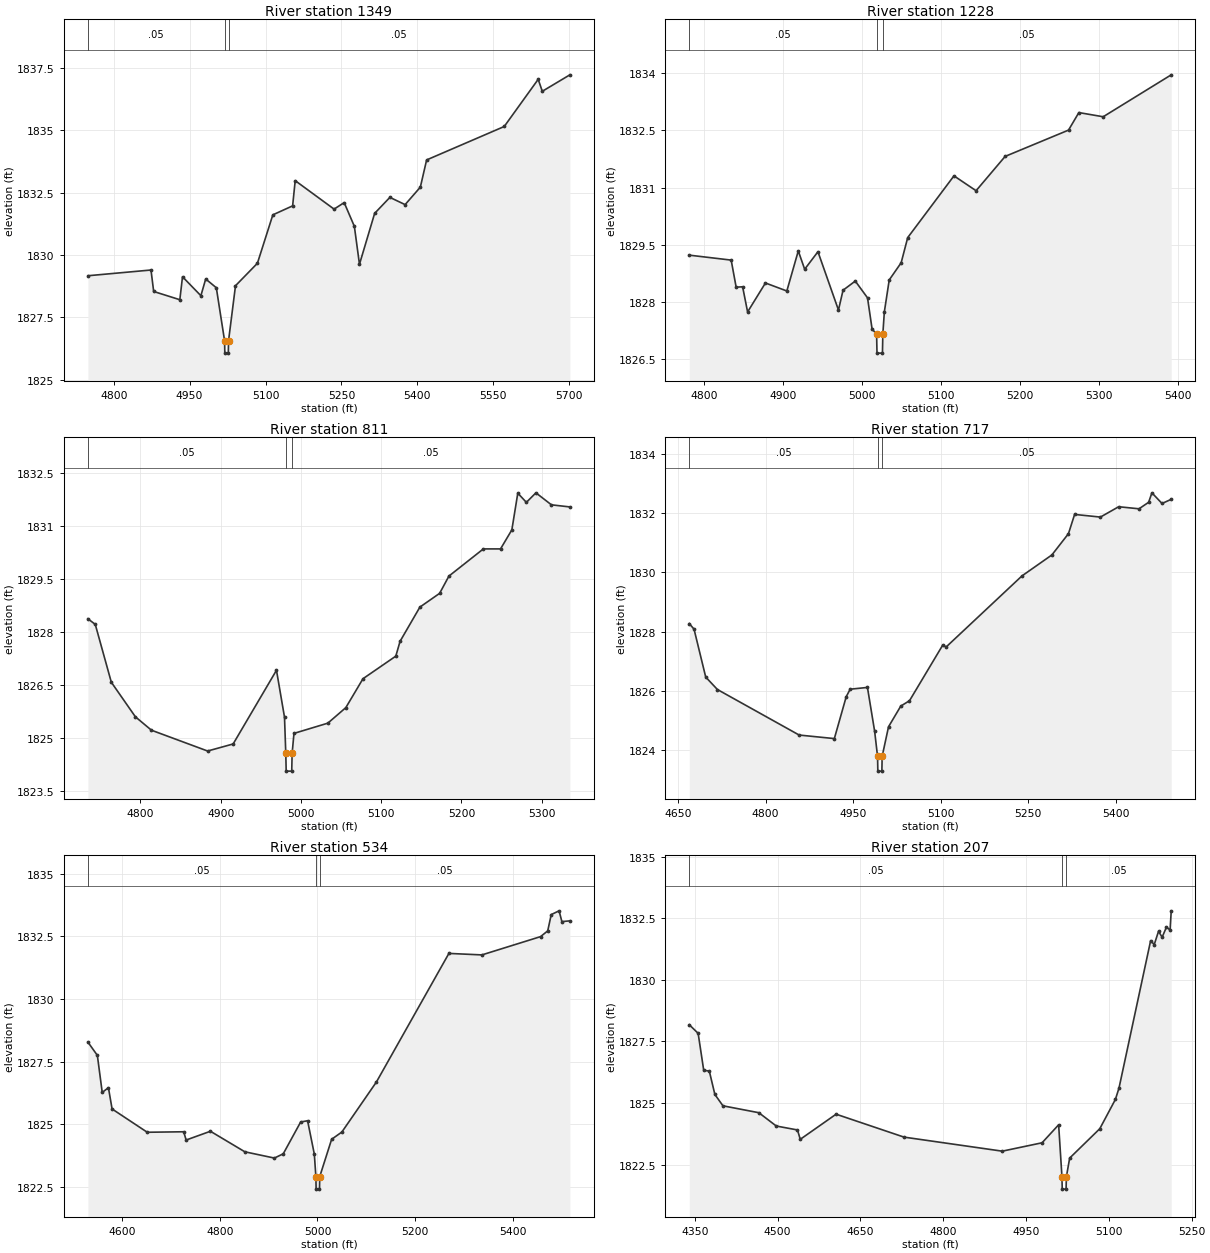
Type RM Length L Ch R = 1,1349,121,121,121
BEGIN DESCRIPTION:
Mapping XS 8cf67820
END DESCRIPTION:
XS GIS Cut Line= 6
      1613709.66      6804387.96      1613766.99      6804391.00
      1613895.96      6804435.40      1614115.15      6804474.46
      1614494.92      6804502.67      1614633.77      6804572.09
#Sta/Elev= 30
  4749.0 1829.17  4873.7 1829.40  4879.0 1828.54  4930.7 1828.21  4936.0 1829.13
  4972.3 1828.37  4981.8 1829.04  5002.8 1828.69  5019.1 1826.57  5019.6 1826.07
  5026.5 1826.07  5027.0 1826.57  5040.7 1828.77  5084.0 1829.67  5114.5 1831.61
  5153.6 1831.97  5158.7 1832.98  5235.5 1831.84  5255.5 1832.10  5275.6 1831.15
  5285.7 1829.63  5315.7 1831.67  5345.8 1832.31  5375.9 1832.02  5406.0 1832.72
  5418.4 1833.81  5571.8 1835.15  5638.9 1837.04  5647.0 1836.56  5701.5 1837.22
#Mann=3,-1,0
  4749.0    0.05       0  5019.1    0.05       0  5027.0    0.05       0
Bank Sta=5019.1,5027
Exp/Cntr=0.3,0.1

Type RM Length L Ch R = 1,1228,417,417,417
BEGIN DESCRIPTION:
Mapping XS 6b54e75d
END DESCRIPTION:
XS GIS Cut Line= 5
      1613700.97      6804394.46      1613746.16      6804409.12
      1613835.20      6804478.80      1613980.60      6804717.51
      1614125.96      6804806.47
#Sta/Elev= 30
  4781.2 1829.23  4834.3 1829.10  4840.6 1828.39  4848.8 1828.40  4855.1 1827.74
  4877.7 1828.50  4904.8 1828.29  4919.3 1829.34  4927.4 1828.86  4944.2 1829.32
  4970.2 1827.79  4976.0 1828.31  4991.5 1828.55  5007.0 1828.11  5012.8 1827.29
  5018.5 1827.16  5019.0 1826.66  5025.9 1826.66  5026.4 1827.16  5028.3 1827.74
  5034.5 1828.58  5049.6 1829.03  5057.9 1829.69  5116.5 1831.31  5144.5 1830.92
  5181.3 1831.82  5261.6 1832.51  5274.7 1832.97  5305.5 1832.86  5391.7 1833.96
#Mann=3,-1,0
  4781.2    0.05       0  5018.5    0.05       0  5026.4    0.05       0
Bank Sta=5018.5,5026.4
Exp/Cntr=0.3,0.1

Type RM Length L Ch R = 1,811,94,94,94
BEGIN DESCRIPTION:
Elm 01 88 811.33
END DESCRIPTION:
XS GIS Cut Line= 4
      1613444.94      6804398.84      1613448.12      6804571.50
      1613529.61      6804608.11      1613845.62      6804729.65
#Sta/Elev= 30
  4734.6 1828.37  4743.8 1828.21  4763.8 1826.57  4793.8 1825.59  4813.8 1825.21
  4883.8 1824.62  4915.6 1824.82  4969.6 1826.91  4979.6 1825.58  4981.2 1824.55
  4981.7 1824.05  4988.6 1824.05  4989.1 1824.55  4991.4 1825.12  5033.6 1825.41
  5056.0 1825.85  5077.4 1826.67  5118.3 1827.31  5123.6 1827.73  5148.3 1828.70
  5172.9 1829.09  5184.5 1829.58  5227.4 1830.35  5248.8 1830.35  5262.9 1830.89
  5270.3 1831.93  5281.0 1831.67  5292.9 1831.94  5312.2 1831.60  5335.2 1831.54
#Mann=3,-1,0
  4734.6    0.05       0  4981.2   0.035       0  4989.1    0.05       0
Bank Sta=4981.2,4989.1
Exp/Cntr=0.3,0.1

Type RM Length L Ch R = 1,717,183,183,183
BEGIN DESCRIPTION:
Mapping XS 64259703
END DESCRIPTION:
XS GIS Cut Line= 4
      1613424.32      6804399.85      1613426.27      6804646.03
      1613594.31      6804760.92      1613935.03      6804919.34
#Sta/Elev= 30
  4669.3 1828.27  4677.5 1828.08  4697.5 1826.46  4717.5 1826.04  4857.5 1824.50
  4917.8 1824.38  4938.2 1825.80  4944.9 1826.05  4974.5 1826.11  4986.8 1824.63
  4991.8 1823.78  4992.3 1823.28  4999.2 1823.28  4999.7 1823.78  5010.6 1824.78
  5031.6 1825.48  5046.5 1825.66  5103.4 1827.54  5109.4 1827.48  5239.1 1829.88
  5290.4 1830.59  5318.8 1831.31  5329.3 1831.96  5373.5 1831.87  5404.8 1832.22
  5439.6 1832.15  5456.1 1832.37  5461.7 1832.69  5479.0 1832.33  5494.8 1832.47
#Mann=3,-1,0
  4669.3    0.05       0  4991.8   0.035       0  4999.7    0.05       0
Bank Sta=4991.8,4999.7
Exp/Cntr=0.3,0.1

Type RM Length L Ch R = 1,534,327,327,327
BEGIN DESCRIPTION:
Mapping XS abdffa95
END DESCRIPTION:
XS GIS Cut Line= 4
      1613395.02      6804398.80      1613344.75      6804791.30
      1613613.84      6805040.86      1613819.98      6805132.00
#Sta/Elev= 30
  4529.3 1828.28  4548.7 1827.75  4558.7 1826.27  4571.4 1826.46  4578.9 1825.61
  4651.0 1824.68  4725.7 1824.70  4730.7 1824.37  4780.5 1824.72  4851.1 1823.90
  4911.6 1823.65  4929.8 1823.82  4965.5 1825.09  4979.7 1825.14  4993.5 1823.81
  4996.7 1822.91  4997.2 1822.41  5004.1 1822.41  5004.6 1822.91  5029.0 1824.40
  5050.0 1824.69  5120.9 1826.69  5269.4 1831.82  5337.0 1831.76  5457.3 1832.49
  5472.0 1832.72  5479.2 1833.37  5495.3 1833.52  5501.0 1833.09  5517.4 1833.12
#Mann=3,-1,0
  4529.3    0.05       0  4996.7   0.035       0  5004.6    0.05       0
Bank Sta=4996.7,5004.6
Exp/Cntr=0.3,0.1

Type RM Length L Ch R = 1,207,0,0,0
BEGIN DESCRIPTION:
Elm 01 88 1450.93
END DESCRIPTION:
XS GIS Cut Line= 5
      1613378.74      6804402.10      1613330.08      6804735.44
      1613231.90      6804973.59      1613231.18      6805122.55
      1613330.83      6805205.05
#Sta/Elev= 30
  4340.1 1828.18  4356.2 1827.83  4366.3 1826.33  4376.4 1826.30  4386.5 1825.35
  4401.1 1824.89  4466.1 1824.61  4497.7 1824.07  4536.1 1823.91  4541.1 1823.53
  4606.0 1824.55  4729.0 1823.62  4906.9 1823.05  4979.0 1823.39  5009.0 1824.12
  5015.0 1822.01  5015.5 1821.51  5022.5 1821.51  5023.0 1822.01  5029.0 1822.77
  5083.5 1823.96  5111.8 1825.15  5118.3 1825.61  5175.6 1831.59  5182.1 1831.43
  5189.9 1831.97  5196.4 1831.73  5204.3 1832.14  5210.8 1832.02  5212.9 1832.80
#Mann=3,-1,0
  4340.1    0.05       0  5015.0    0.05       0  5023.0    0.05       0
Bank Sta=5015,5023
Exp/Cntr=0.3,0.1

Chan Stop Cuts=-1