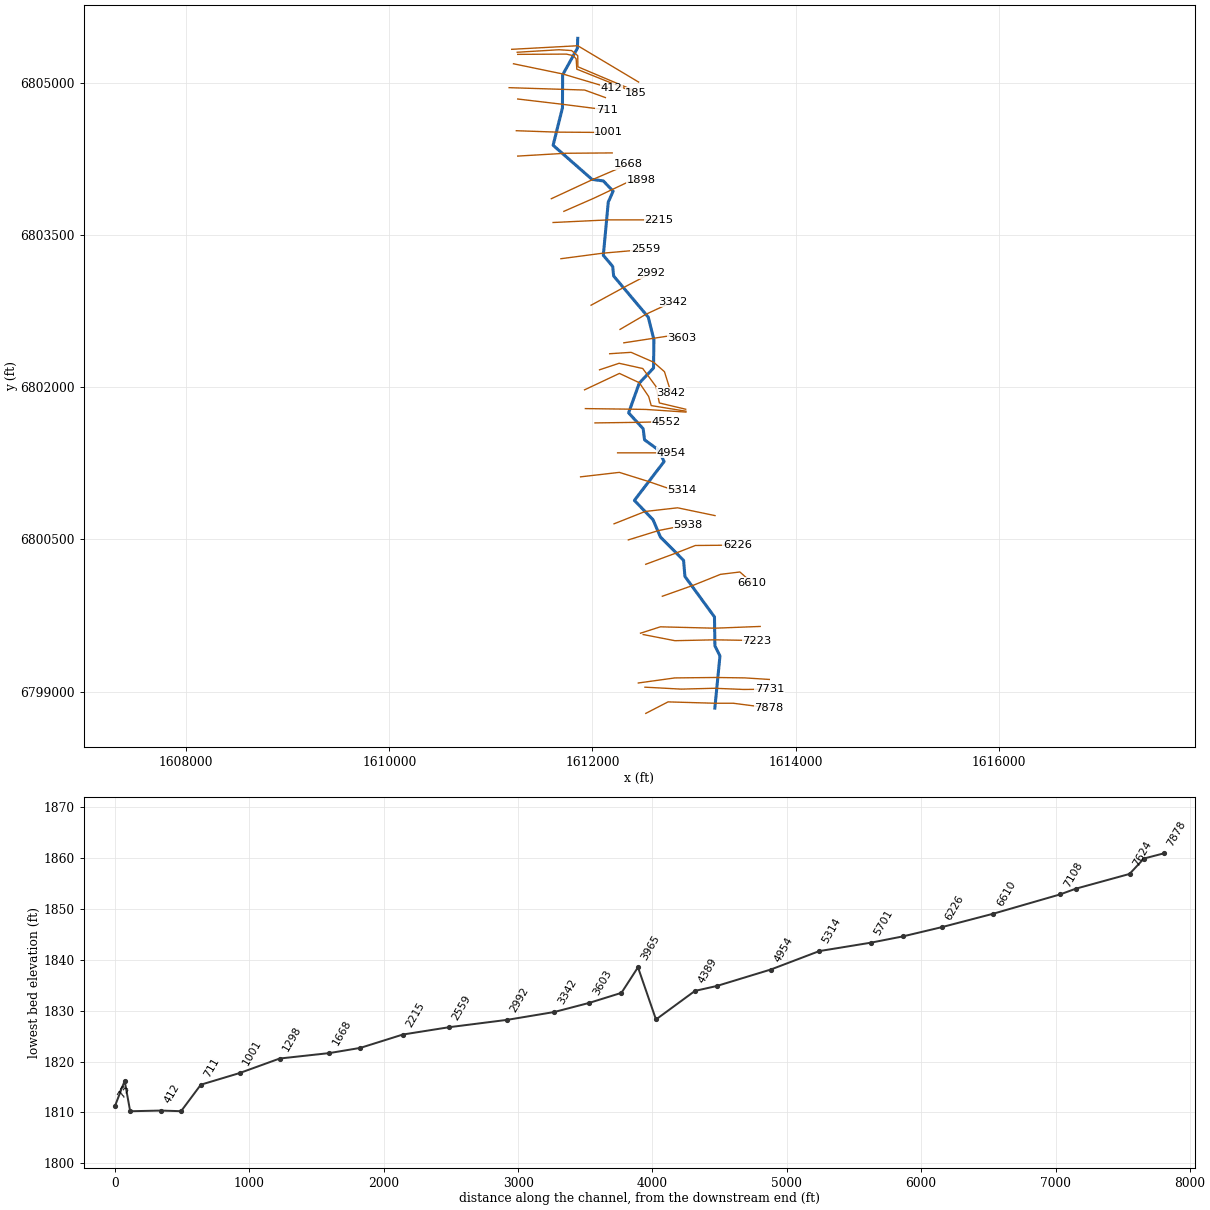
--- Elm 01 89.prj (project) ---

Proj Title=Elm 01 89 Base Level Engineering
Current Plan=p01
Default Exp/Contr=0.3,0.1
English Units
Geom File=g01
Flow File=f01
Plan File=p01
BEGIN DESCRIPTION:
Elm 01 89
END DESCRIPTION:

--- Elm 01 89.p01 (plan) ---

Plan Title=Multiple Run
Short Identifier=Multiple
Geom File=g01
Flow File=f01
Subcritical Flow
K Sum by GR= 0
Std Step Tol= 0.01
Critical Tol= 0.01
Num of Std Step Trials= 20
Max Error Tol= 0.3
Flow Tol Ratio= 0.001
Split Flow NTrial= 30
Split Flow Tol= 0.02
Split Flow Ratio= 0.02
Log Output Level= 0
Friction Slope Method= 1
Unsteady Friction Slope Method= 2
Unsteady Bridges Friction Slope Method= 1
Parabolic Critical Depth
Global Vel Dist=  1 , 1 , 1
Global Log Level= 0
CheckData=True
Encroach Param= -1, 0, 0, 0
BEGIN DESCRIPTION:
Multiple Run
END DESCRIPTION:

--- Elm 01 89.f01 (steady flow) ---

Flow Title=Multiple
Number of Profiles=7
Profile Names=10-year,25-year,50-year,1pct_min,100-year,1pct_plu,500-year
River Rch & RM= Elm 01 89,Reach-1,7878
     295     420     526     409     655     902    1030
River Rch & RM= Elm 01 89,Reach-1,7624
     363     519     652     508     813    1120    1280
Boundary for River Rch & Prof#=Elm 01 89,Reach-1,1
Up Type=0
Dn Type=3
Dn Slope=0.001
Boundary for River Rch & Prof#=Elm 01 89,Reach-1,2
Up Type=0
Dn Type=3
Dn Slope=0.001
Boundary for River Rch & Prof#=Elm 01 89,Reach-1,3
Up Type=0
Dn Type=3
Dn Slope=0.001
Boundary for River Rch & Prof#=Elm 01 89,Reach-1,4
Up Type=0
Dn Type=3
Dn Slope=0.001
Boundary for River Rch & Prof#=Elm 01 89,Reach-1,5
Up Type=0
Dn Type=3
Dn Slope=0.001
Boundary for River Rch & Prof#=Elm 01 89,Reach-1,6
Up Type=0
Dn Type=3
Dn Slope=0.001
Boundary for River Rch & Prof#=Elm 01 89,Reach-1,7
Up Type=0
Dn Type=3
Dn Slope=0.001

--- Elm 01 89.g01 (geometry) ---

Geom Title=Existing Conditions

River Reach=Elm 01 89,Reach-1
Reach XY= 30
      1613205.00      6798838.00      1613255.44      6799351.82
      1613205.68      6799451.92      1613201.45      6799736.53
      1612910.48      6800135.56      1612897.18      6800294.19
      1612668.62      6800524.79      1612596.86      6800694.06
      1612412.77      6800884.59      1612705.38      6801267.81
      1612649.41      6801382.39      1612512.86      6801481.81
      1612499.48      6801590.43      1612356.09      6801747.63
      1612460.83      6802040.30      1612601.46      6802189.46
      1612604.93      6802467.97      1612549.53      6802690.45
      1612208.66      6803096.19      1612199.22      6803190.30
      1612106.91      6803299.95      1612155.70      6803824.09
      1612203.39      6803931.98      1612107.44      6804032.48
      1611995.21      6804048.52      1611612.69      6804384.33
      1611704.48      6804753.22      1611706.38      6805078.34
      1611851.38      6805339.47      1611855.00      6805438.00

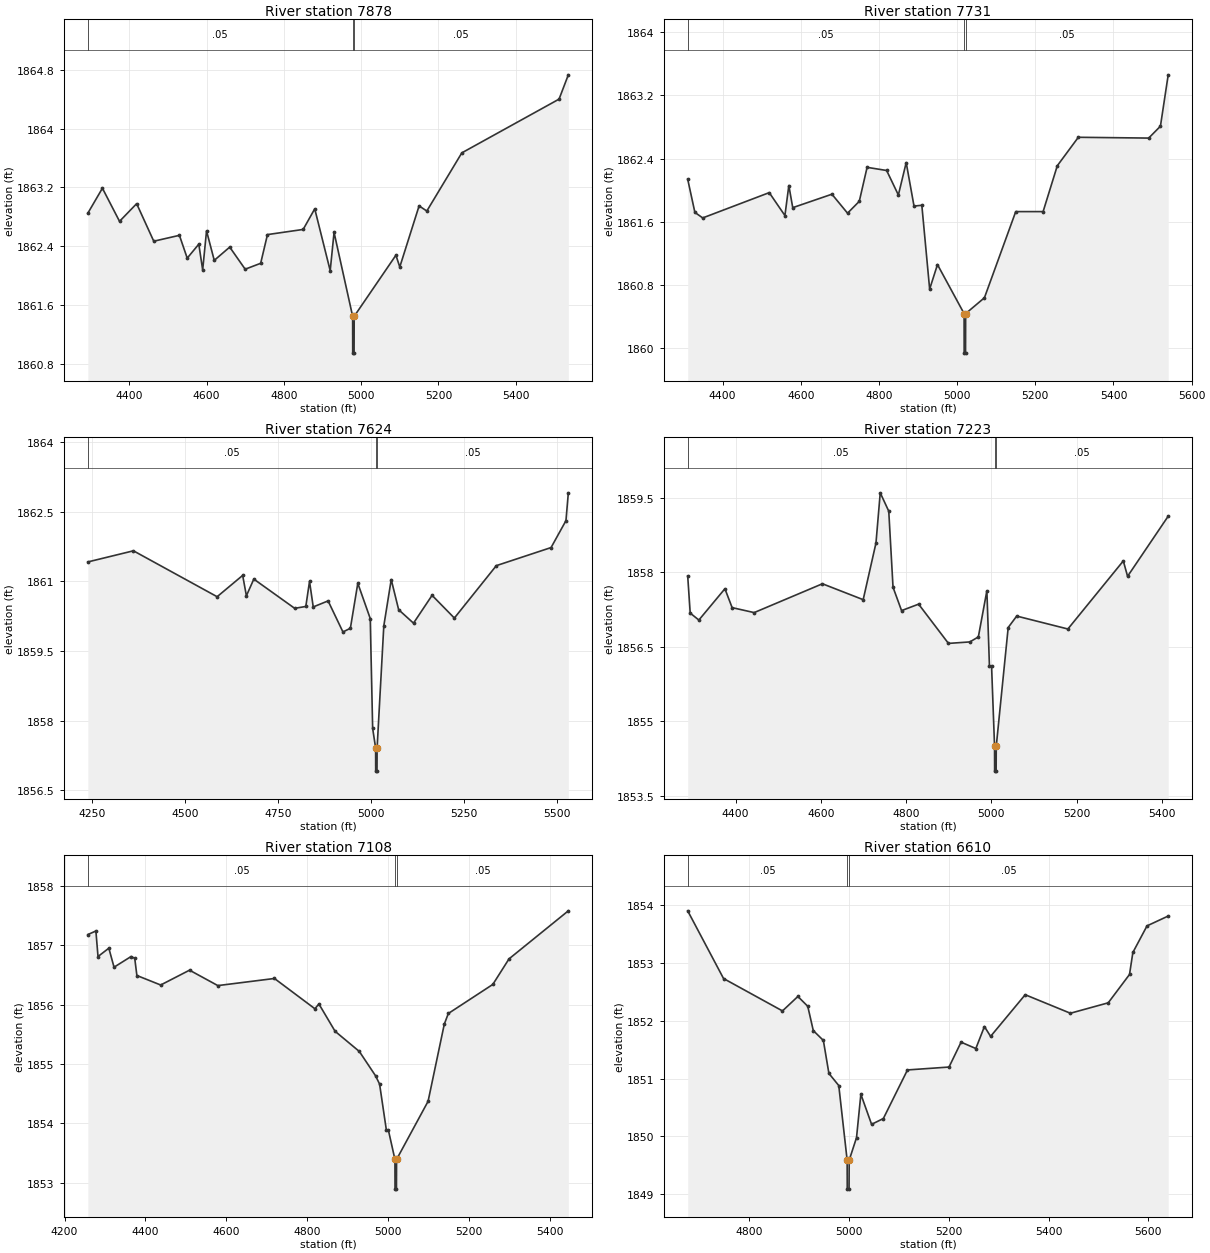
Type RM Length L Ch R = 1,7878,147,147,147
BEGIN DESCRIPTION:
Elm 01 89 7568.309
END DESCRIPTION:
XS GIS Cut Line= 5
      1612525.26      6798786.23      1612744.37      6798899.46
      1613205.04      6798885.99      1613386.85      6798885.99
      1613738.41      6798840.50
#Sta/Elev= 30
  4292.5 1862.85  4330.3 1863.19  4374.6 1862.74  4418.9 1862.98  4463.2 1862.47
  4529.6 1862.55  4549.8 1862.24  4579.8 1862.43  4589.8 1862.08  4599.8 1862.61
  4619.8 1862.21  4659.8 1862.39  4699.8 1862.09  4739.9 1862.17  4757.5 1862.56
  4849.9 1862.63  4879.9 1862.91  4919.9 1862.07  4929.9 1862.59  4978.0 1861.45
  4978.2 1860.95  4981.7 1860.95  4982.0 1861.45  5090.0 1862.28  5100.0 1862.12
  5150.0 1862.95  5170.0 1862.88  5260.6 1863.67  5512.3 1864.40  5536.3 1864.73
#Mann=3,-1,0
  4292.5    0.05       0  4978.0    0.05       0  4982.0    0.05       0
Bank Sta=4978,4982
Exp/Cntr=0.3,0.1

Type RM Length L Ch R = 1,7731,107,107,107
BEGIN DESCRIPTION:
Elm 01 89 7731.04
END DESCRIPTION:
XS GIS Cut Line= 5
      1612516.67      6799044.49      1612872.41      6799025.32
      1613202.02      6799033.56      1613490.80      6799021.85
      1613744.89      6799024.96
#Sta/Elev= 30
  4310.9 1862.14  4329.3 1861.72  4349.3 1861.65  4519.5 1861.97  4559.6 1861.68
  4569.6 1862.06  4579.6 1861.78  4679.8 1861.95  4719.8 1861.71  4749.8 1861.86
  4769.8 1862.29  4819.8 1862.25  4849.8 1861.94  4869.8 1862.35  4889.8 1861.80
  4909.8 1861.81  4929.8 1860.75  4949.8 1861.06  5017.9 1860.44  5018.1 1859.94
  5021.6 1859.94  5021.9 1860.44  5069.9 1860.64  5150.0 1861.73  5220.0 1861.73
  5256.3 1862.31  5310.1 1862.67  5490.1 1862.66  5520.1 1862.81  5540.0 1863.46
#Mann=3,-1,0
  4310.9    0.05       0  5017.9    0.03       0  5021.9    0.05       0
Bank Sta=5017.9,5021.9
Exp/Cntr=0.3,0.1

Type RM Length L Ch R = 1,7624,401,401,401
BEGIN DESCRIPTION:
Elm 01 89 7623.89
END DESCRIPTION:
XS GIS Cut Line= 5
      1612451.49      6799085.72      1612811.76      6799135.64
      1613208.53      6799139.90      1613499.70      6799135.93
      1613741.40      6799120.54
#Sta/Elev= 30
  4237.4 1861.42  4360.2 1861.66  4585.6 1860.67  4654.4 1861.13  4664.4 1860.69
  4684.4 1861.05  4794.4 1860.42  4824.4 1860.46  4834.4 1861.00  4844.4 1860.45
  4884.4 1860.58  4924.4 1859.91  4944.4 1859.99  4964.4 1860.96  4997.9 1860.20
  5004.4 1857.83  5012.4 1857.41  5012.6 1856.91  5016.1 1856.91  5016.4 1857.41
  5034.4 1860.04  5054.4 1861.04  5074.4 1860.39  5114.4 1860.10  5164.4 1860.70
  5224.4 1860.21  5337.4 1861.34  5484.8 1861.73  5524.9 1862.31  5531.3 1862.91
#Mann=3,-1,0
  4237.4    0.05       0  5012.4    0.05       0  5016.4    0.05       0
Bank Sta=5012.4,5016.4
Exp/Cntr=0.3,0.1

Type RM Length L Ch R = 1,7223,115,115,115
BEGIN DESCRIPTION:
Elm 01 89 7222.52
END DESCRIPTION:
XS GIS Cut Line= 4
      1612499.26      6799563.16      1612811.71      6799502.47
      1613202.06      6799510.95      1613620.27      6799504.01
#Sta/Elev= 30
  4287.7 1857.93  4293.6 1857.18  4313.9 1857.04  4375.0 1857.67  4391.9 1857.29
  4443.6 1857.19  4603.7 1857.77  4699.3 1857.45  4729.3 1858.59  4739.3 1859.60
  4759.3 1859.23  4769.3 1857.70  4789.3 1857.23  4829.3 1857.36  4899.3 1856.57
  4949.4 1856.60  4969.4 1856.70  4989.4 1857.63  4995.4 1856.12  5000.4 1856.12
  5007.4 1854.50  5007.6 1854.00  5011.1 1854.00  5011.4 1854.50  5039.4 1856.89
  5059.4 1857.12  5179.4 1856.86  5309.4 1858.23  5319.4 1857.92  5414.7 1859.13
#Mann=3,-1,0
  4287.7    0.05       0  5007.4    0.05       0  5011.4    0.05       0
Bank Sta=5007.4,5011.4
Exp/Cntr=0.3,0.1

Type RM Length L Ch R = 1,7108,498,498,498
BEGIN DESCRIPTION:
Elm 01 89 7107.81
END DESCRIPTION:
XS GIS Cut Line= 4
      1612473.19      6799576.17      1612668.53      6799639.11
      1613203.80      6799625.54      1613651.70      6799642.83
#Sta/Elev= 30
  4257.6 1857.18  4277.6 1857.24  4282.8 1856.81  4309.6 1856.95  4322.5 1856.63
  4364.6 1856.81  4373.7 1856.78  4379.0 1856.49  4437.9 1856.33  4509.3 1856.58
  4579.3 1856.32  4719.4 1856.44  4819.4 1855.93  4829.4 1856.01  4869.4 1855.55
  4929.4 1855.21  4969.5 1854.80  4979.5 1854.66  4996.4 1853.88  5001.4 1853.88
  5017.5 1853.39  5017.7 1852.89  5021.2 1852.89  5021.5 1853.39  5099.5 1854.37
  5139.6 1855.67  5149.6 1855.85  5259.7 1856.34  5299.7 1856.77  5446.5 1857.58
#Mann=3,-1,0
  4257.6    0.05       0  5017.5    0.05       0  5021.5    0.05       0
Bank Sta=5017.5,5021.5
Exp/Cntr=0.3,0.1

Type RM Length L Ch R = 1,6610,384,384,384
BEGIN DESCRIPTION:
Elm 01 89 6609.51
END DESCRIPTION:
XS GIS Cut Line= 5
      1612688.07      6799940.42      1612992.77      6800048.50
      1613261.14      6800156.32      1613451.95      6800179.48
      1613570.64      6800073.74
#Sta/Elev= 30
  4676.2 1853.90  4748.1 1852.73  4866.3 1852.17  4897.2 1852.42  4917.0 1852.25
  4928.1 1851.83  4948.3 1851.66  4959.4 1851.09  4979.2 1850.88  4996.0 1849.59
  4996.2 1849.09  4999.8 1849.09  5000.1 1849.59  5014.8 1849.98  5023.5 1850.73
  5045.0 1850.21  5068.6 1850.31  5117.0 1851.15  5200.3 1851.20  5224.5 1851.63
  5254.1 1851.52  5271.3 1851.90  5283.7 1851.73  5353.1 1852.45  5443.7 1852.13
  5519.6 1852.31  5562.3 1852.80  5569.0 1853.18  5597.4 1853.64  5639.9 1853.81
#Mann=3,-1,0
  4676.2    0.05       0  4996.0    0.05       0  5000.1    0.05       0
Bank Sta=4996,5000.1
Exp/Cntr=0.3,0.1

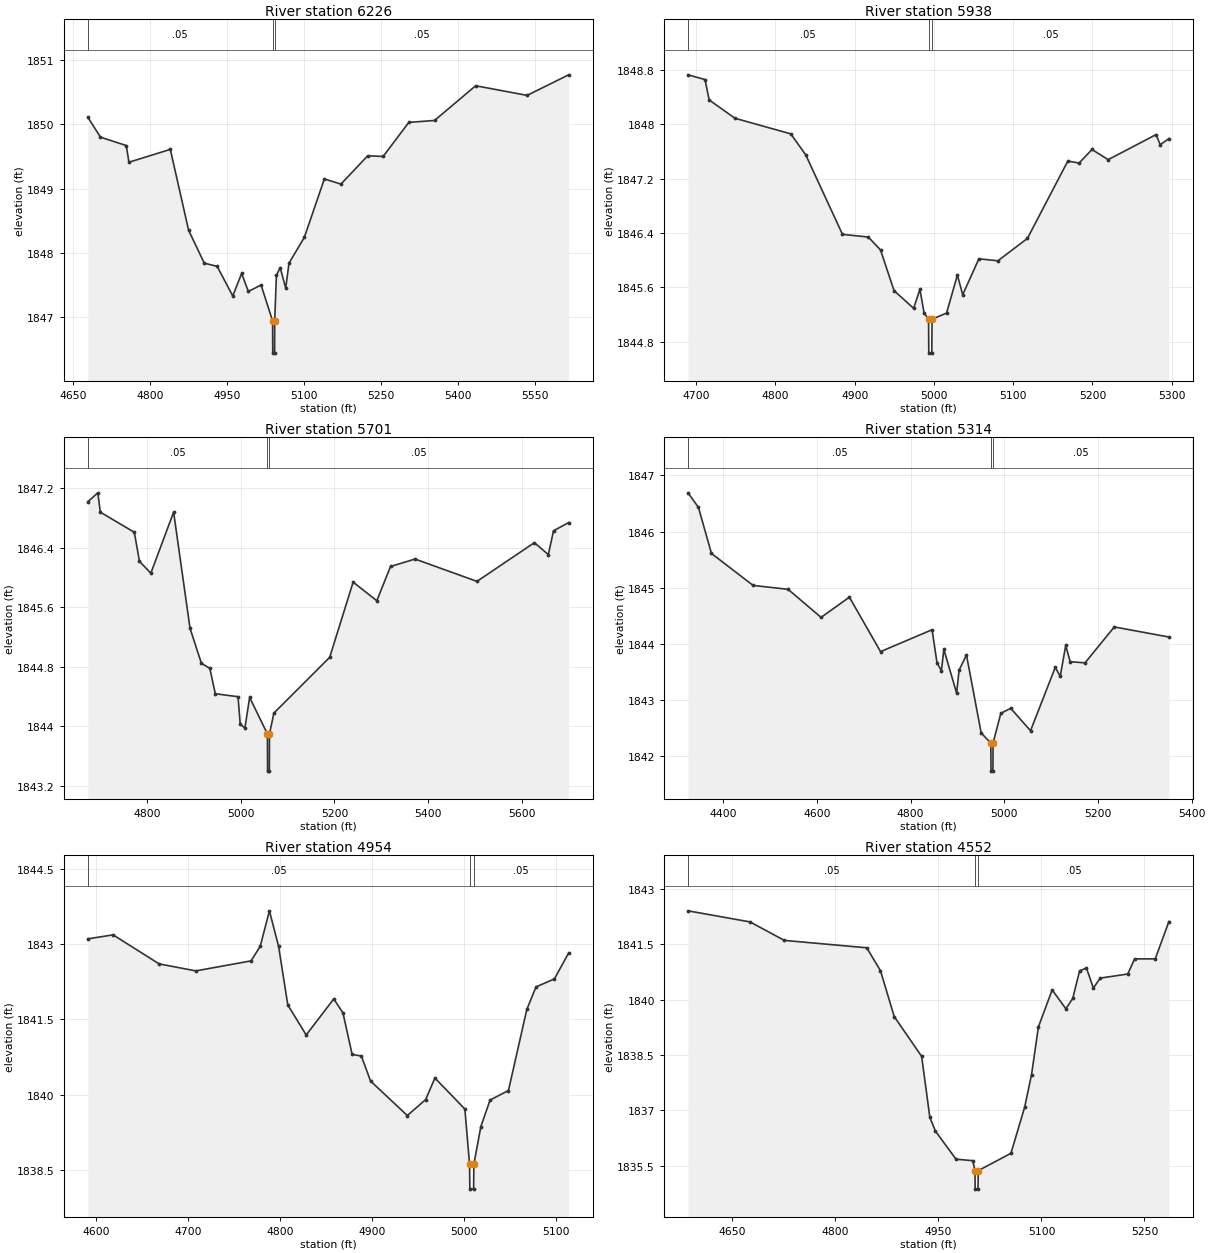
Type RM Length L Ch R = 1,6226,288,288,288
BEGIN DESCRIPTION:
Elm 01 89 6226.4
END DESCRIPTION:
XS GIS Cut Line= 4
      1612524.55      6800255.30      1612828.41      6800368.16
      1613013.32      6800440.58      1613425.87      6800444.24
#Sta/Elev= 30
  4679.4 1850.11  4704.0 1849.80  4754.1 1849.67  4759.4 1849.41  4839.8 1849.61
  4875.5 1848.35  4905.9 1847.84  4930.9 1847.79  4961.3 1847.33  4978.6 1847.68
  4991.6 1847.40  5016.4 1847.50  5038.8 1846.94  5039.1 1846.44  5042.7 1846.44
  5042.9 1846.94  5046.2 1847.65  5053.6 1847.77  5064.3 1847.45  5070.7 1847.84
  5100.5 1848.24  5139.5 1849.15  5171.7 1849.07  5223.8 1849.51  5253.8 1849.50
  5303.8 1850.03  5353.8 1850.06  5433.8 1850.60  5533.8 1850.45  5614.7 1850.77
#Mann=3,-1,0
  4679.4    0.05       0  5038.8    0.05       0  5042.9    0.05       0
Bank Sta=5038.8,5042.9
Exp/Cntr=0.3,0.1

Type RM Length L Ch R = 1,5938,237,237,237
BEGIN DESCRIPTION:
Elm 01 89 5937.72
END DESCRIPTION:
XS GIS Cut Line= 3
      1612353.14      6800495.54      1612650.45      6800587.78
      1612940.11      6800645.27
#Sta/Elev= 30
  4689.8 1848.73  4711.2 1848.66  4716.4 1848.36  4749.0 1848.09  4819.4 1847.86
  4838.3 1847.55  4884.6 1846.38  4917.2 1846.34  4932.6 1846.15  4949.7 1845.55
  4974.4 1845.29  4982.3 1845.57  4987.6 1845.22  4993.2 1845.13  4993.5 1844.63
  4997.3 1844.63  4997.6 1845.13  5015.9 1845.22  5029.6 1845.78  5036.3 1845.49
  5056.7 1846.02  5080.7 1845.99  5117.9 1846.32  5168.9 1847.46  5183.1 1847.43
  5199.4 1847.63  5219.8 1847.48  5280.3 1847.85  5285.4 1847.70  5296.4 1847.79
#Mann=3,-1,0
  4689.8    0.05       0  4993.2    0.05       0  4997.6    0.05       0
Bank Sta=4993.2,4997.6
Exp/Cntr=0.3,0.1

Type RM Length L Ch R = 1,5701,387,387,387
BEGIN DESCRIPTION:
Elm 01 89 5701.45
END DESCRIPTION:
XS GIS Cut Line= 4
      1612212.69      6800654.17      1612518.73      6800775.71
      1612838.19      6800811.93      1613206.76      6800735.03
#Sta/Elev= 30
  4673.0 1847.02  4694.3 1847.14  4699.7 1846.88  4772.3 1846.61  4783.3 1846.22
  4807.6 1846.06  4856.3 1846.88  4891.3 1845.32  4915.6 1844.85  4933.7 1844.78
  4945.3 1844.44  4993.9 1844.40  4998.6 1844.03  5008.6 1843.98  5018.7 1844.39
  5056.7 1843.90  5057.0 1843.40  5060.8 1843.40  5061.1 1843.90  5070.5 1844.18
  5189.8 1844.93  5239.8 1845.94  5290.4 1845.69  5319.7 1846.15  5372.1 1846.25
  5504.4 1845.95  5627.0 1846.47  5656.9 1846.31  5667.9 1846.63  5700.3 1846.74
#Mann=3,-1,0
  4673.0    0.05       0  5056.7    0.05       0  5061.1    0.05       0
Bank Sta=5056.7,5061.1
Exp/Cntr=0.3,0.1

Type RM Length L Ch R = 1,5314,360,360,360
BEGIN DESCRIPTION:
Elm 01 89 5313.74
END DESCRIPTION:
XS GIS Cut Line= 5
      1611882.94      6801116.98      1612264.41      6801161.02
      1612543.68      6801073.67      1612745.25      6801004.38
      1612880.56      6800986.85
#Sta/Elev= 30
  4325.2 1846.69  4347.4 1846.43  4375.1 1845.61  4464.0 1845.04  4538.7 1844.97
  4609.1 1844.47  4669.5 1844.83  4736.0 1843.86  4846.0 1844.25  4856.5 1843.66
  4865.9 1843.52  4871.1 1843.90  4898.4 1843.12  4903.6 1843.53  4919.4 1843.80
  4950.8 1842.41  4971.4 1842.23  4971.8 1841.73  4975.8 1841.73  4976.1 1842.23
  4992.7 1842.76  5013.8 1842.85  5056.1 1842.45  5108.9 1843.58  5119.5 1843.42
  5131.2 1843.97  5140.7 1843.68  5172.4 1843.66  5234.9 1844.30  5351.4 1844.12
#Mann=3,-1,0
  4325.2    0.05       0  4971.4    0.05       0  4976.1    0.05       0
Bank Sta=4971.4,4976.1
Exp/Cntr=0.3,0.1

Type RM Length L Ch R = 1,4954,402,402,402
BEGIN DESCRIPTION:
Elm 01 89 4953.85
END DESCRIPTION:
XS GIS Cut Line= 3
      1612247.49      6801353.73      1612657.62      6801353.73
      1612770.49      6801354.45
#Sta/Elev= 30
  4590.7 1843.11  4618.2 1843.19  4668.2 1842.61  4708.2 1842.47  4768.2 1842.67
  4778.2 1842.96  4788.2 1843.67  4798.2 1842.96  4808.2 1841.79  4828.2 1841.19
  4858.2 1841.91  4868.2 1841.63  4878.2 1840.80  4888.2 1840.77  4898.2 1840.27
  4938.2 1839.58  4958.2 1839.90  4968.2 1840.33  5000.8 1839.71  5005.9 1838.61
  5006.2 1838.11  5010.3 1838.11  5010.6 1838.61  5018.2 1839.36  5028.2 1839.89
  5048.2 1840.08  5068.2 1841.70  5078.2 1842.15  5098.2 1842.31  5113.7 1842.83
#Mann=3,-1,0
  4590.7    0.05       0  5005.9    0.05       0  5010.6    0.05       0
Bank Sta=5005.9,5010.6
Exp/Cntr=0.3,0.1

Type RM Length L Ch R = 1,4552,163,163,163
BEGIN DESCRIPTION:
Elm 01 89 4552.14
END DESCRIPTION:
XS GIS Cut Line= 4
      1612024.84      6801648.43      1612439.35      6801653.86
      1612631.77      6801658.48      1612724.94      6801657.34
#Sta/Elev= 30
  4585.4 1842.40  4675.6 1842.10  4725.6 1841.60  4845.6 1841.40  4865.6 1840.78
  4885.6 1839.54  4925.6 1838.46  4937.5 1836.81  4945.6 1836.44  4975.6 1835.68
  5000.0 1835.64  5003.2 1835.37  5003.5 1834.87  5007.6 1834.87  5008.0 1835.37
  5055.6 1835.84  5075.6 1837.09  5085.6 1837.97  5095.6 1839.26  5115.6 1840.26
  5135.6 1839.75  5145.6 1840.03  5155.6 1840.78  5165.6 1840.85  5175.6 1840.31
  5185.7 1840.58  5225.7 1840.69  5235.7 1841.10  5265.7 1841.10  5285.6 1842.11
#Mann=3,-1,0
  4585.4    0.05       0  5003.2    0.03       0  5008.0    0.05       0
Bank Sta=5003.2,5008
Exp/Cntr=0.3,0.1

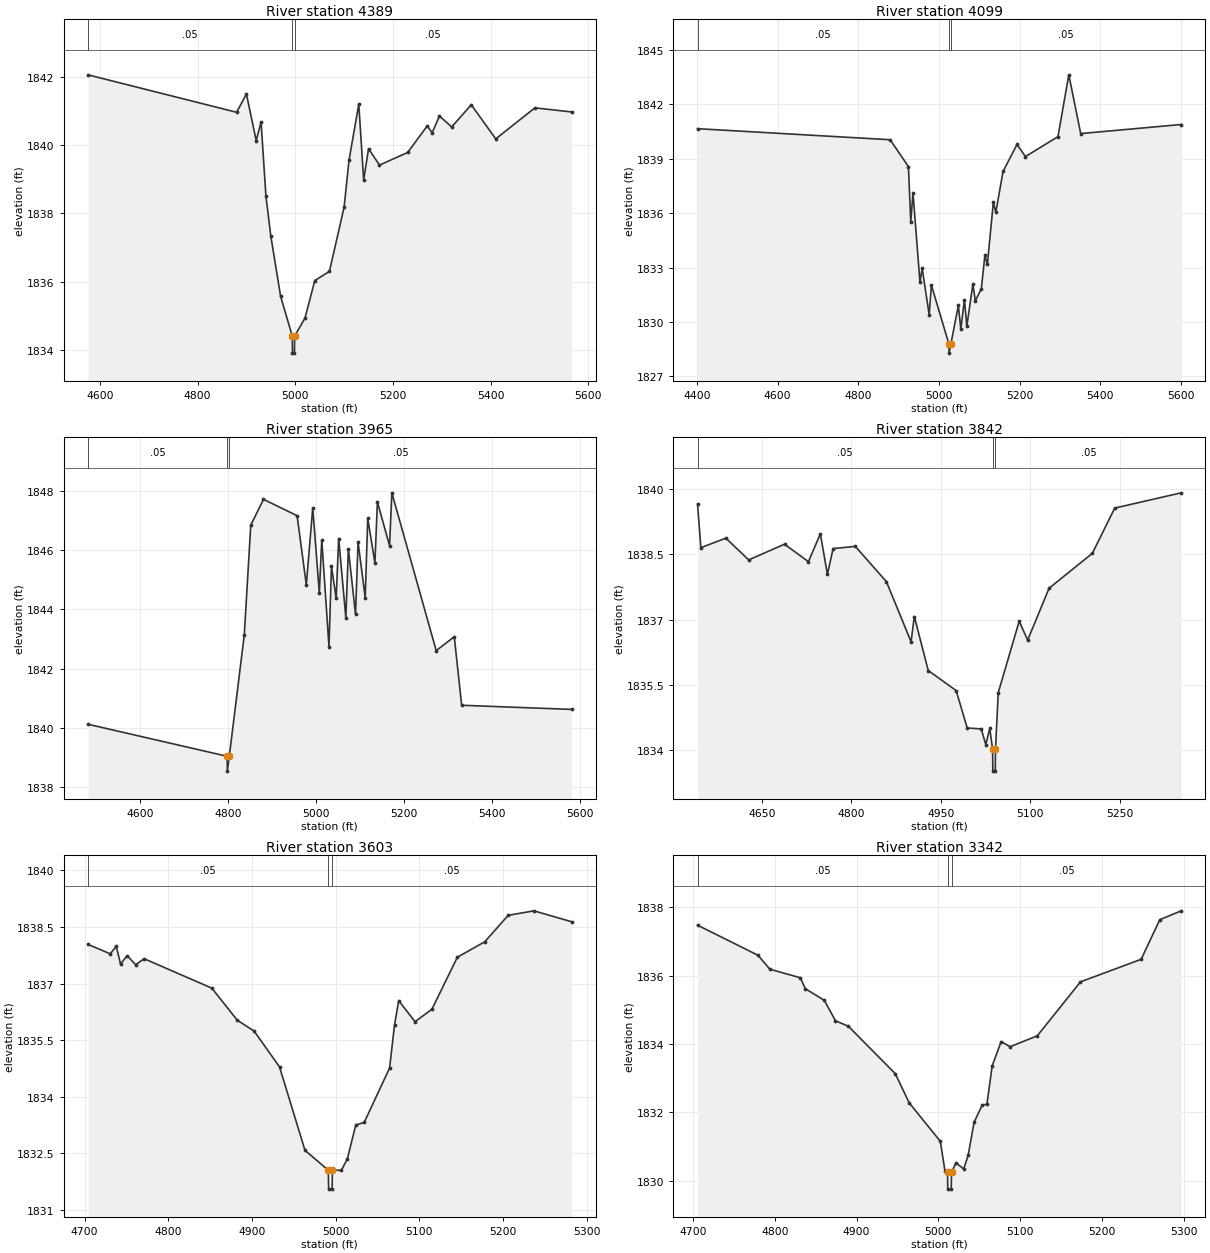
Type RM Length L Ch R = 1,4389,290,290,290
BEGIN DESCRIPTION:
Elm 01 89 4389.13
END DESCRIPTION:
XS GIS Cut Line= 4
      1611930.50      6801789.49      1612352.55      6801784.07
      1612527.44      6801781.18      1612920.17      6801755.01
#Sta/Elev= 30
  4575.4 1842.07  4879.9 1840.97  4899.9 1841.51  4919.9 1840.14  4929.9 1840.68
  4939.9 1838.50  4949.9 1837.33  4969.9 1835.57  4993.8 1834.40  4994.2 1833.90
  4998.3 1833.90  4998.6 1834.40  5019.9 1834.93  5039.9 1836.03  5069.9 1836.30
  5099.9 1838.18  5110.0 1839.56  5130.0 1841.21  5140.0 1838.98  5150.0 1839.90
  5172.4 1839.42  5230.1 1839.79  5270.2 1840.57  5280.2 1840.37  5295.3 1840.86
  5320.3 1840.54  5360.4 1841.19  5410.5 1840.19  5490.7 1841.10  5566.0 1840.98
#Mann=3,-1,0
  4575.4    0.05       0  4993.8    0.05       0  4998.6    0.05       0
Bank Sta=4993.8,4998.6
Exp/Cntr=0.3,0.1

Type RM Length L Ch R = 1,4099,134,134,134
BEGIN DESCRIPTION:
Elm 01 89 4099.07
END DESCRIPTION:
XS GIS Cut Line= 6
      1611921.97      6801974.17      1612265.69      6802136.20
      1612461.38      6802044.37      1612553.39      6801908.96
      1612578.60      6801819.23      1612920.13      6801763.70
#Sta/Elev= 30
  4401.6 1840.66  4879.0 1840.05  4924.4 1838.57  4930.2 1835.52  4935.7 1837.13
  4953.0 1832.19  4958.5 1832.96  4975.8 1830.40  4981.3 1832.03  5024.8 1828.78
  5025.2 1828.28  5029.6 1828.78  5048.2 1830.91  5054.3 1829.61  5063.2 1831.23
  5069.2 1829.77  5084.2 1832.09  5090.2 1831.17  5105.1 1831.82  5114.0 1833.67
  5120.1 1833.17  5135.0 1836.61  5141.1 1836.05  5159.0 1838.30  5193.6 1839.79
  5214.4 1839.12  5295.1 1840.22  5322.0 1843.63  5351.5 1840.39  5600.7 1840.89
#Mann=3,-1,0
  4401.6    0.05       0  5024.8    0.05       0  5029.6    0.05       0
Bank Sta=5024.8,5029.6
Exp/Cntr=0.3,0.1

Type RM Length L Ch R = 1,3965,123,123,123
BEGIN DESCRIPTION:
Elm 01 89 3965.04
END DESCRIPTION:
XS GIS Cut Line= 6
      1612069.60      6802171.67      1612262.56      6802236.05
      1612495.23      6802184.35      1612625.44      6802007.26
      1612658.72      6801845.02      1612918.11      6801783.21
#Sta/Elev= 30
  4482.1 1840.13  4798.3 1839.05  4798.7 1838.55  4803.1 1839.05  4837.2 1843.14
  4851.9 1846.84  4880.8 1847.71  4957.2 1847.16  4978.1 1844.83  4992.7 1847.42
  5007.6 1844.56  5013.2 1846.34  5029.6 1842.75  5035.2 1845.46  5045.9 1844.37
  5051.6 1846.39  5067.9 1843.72  5073.6 1846.04  5089.9 1843.83  5095.6 1846.27
  5111.9 1844.40  5117.6 1847.07  5133.9 1845.57  5139.6 1847.62  5167.2 1846.15
  5172.4 1847.93  5273.2 1842.61  5314.2 1843.08  5331.0 1840.77  5580.9 1840.63
#Mann=3,-1,0
  4482.1    0.05       0  4798.3    0.05       0  4803.1    0.05       0
Bank Sta=4798.3,4803.1
Exp/Cntr=0.3,0.1

Type RM Length L Ch R = 1,3842,239,239,239
BEGIN DESCRIPTION:
Elm 01 89 3841.92
END DESCRIPTION:
XS GIS Cut Line= 5
      1612169.44      6802330.09      1612380.29      6802343.98
      1612602.01      6802246.85      1612708.78      6802153.10
      1612773.87      6801947.41
#Sta/Elev= 30
  4542.1 1839.65  4547.7 1838.65  4589.6 1838.87  4627.9 1838.37  4688.0 1838.73
  4728.1 1838.33  4748.1 1838.97  4759.9 1838.04  4769.5 1838.63  4806.7 1838.68
  4858.9 1837.87  4900.2 1836.49  4905.7 1837.07  4929.0 1835.83  4975.8 1835.37
  4994.4 1834.51  5017.9 1834.49  5025.5 1834.13  5032.2 1834.50  5037.0 1834.02
  5037.3 1833.52  5041.4 1833.52  5041.8 1834.02  5046.4 1835.32  5081.5 1836.96
  5095.8 1836.53  5131.7 1837.72  5204.2 1838.52  5241.8 1839.56  5353.3 1839.91
#Mann=3,-1,0
  4542.1    0.05       0  5037.0    0.05       0  5041.8    0.05       0
Bank Sta=5037,5041.8
Exp/Cntr=0.3,0.1

Type RM Length L Ch R = 1,3603,261,261,261
BEGIN DESCRIPTION:
Mapping XS 66c19ed0
END DESCRIPTION:
XS GIS Cut Line= 3
      1612308.69      6802437.57      1612777.44      6802509.18
      1612879.40      6802489.65
#Sta/Elev= 30
  4704.0 1838.04  4730.6 1837.79  4737.8 1837.99  4742.9 1837.52  4750.8 1837.74
  4761.0 1837.50  4771.1 1837.66  4852.0 1836.88  4882.4 1836.03  4902.6 1835.74
  4932.9 1834.79  4963.3 1832.58  4991.2 1832.05  4991.6 1831.55  4995.7 1831.55
  4996.1 1832.05  5006.8 1832.05  5013.9 1832.35  5024.0 1833.25  5034.1 1833.32
  5064.4 1834.76  5070.3 1835.90  5075.3 1836.55  5094.8 1835.99  5115.0 1836.32
  5145.4 1837.70  5178.2 1838.11  5206.1 1838.81  5236.8 1838.93  5282.0 1838.64
#Mann=3,-1,0
  4704.0    0.05       0  4991.2    0.05       0  4996.1    0.05       0
Bank Sta=4991.2,4996.1
Exp/Cntr=0.3,0.1

Type RM Length L Ch R = 1,3342,350,350,350
BEGIN DESCRIPTION:
Elm 01 89 3342.18
END DESCRIPTION:
XS GIS Cut Line= 3
      1612271.31      6802569.79      1612525.18      6802718.20
      1612794.38      6802843.74
#Sta/Elev= 30
  4705.7 1837.48  4779.5 1836.60  4794.1 1836.19  4831.3 1835.94  4837.4 1835.62
  4860.6 1835.28  4874.3 1834.68  4890.0 1834.52  4947.4 1833.13  4964.3 1832.28
  5002.4 1831.15  5008.1 1830.28  5011.2 1830.25  5011.5 1829.75  5015.7 1829.75
  5016.1 1830.25  5021.6 1830.52  5031.0 1830.34  5036.5 1830.75  5043.7 1831.71
  5053.8 1832.22  5059.3 1832.23  5065.8 1833.36  5076.7 1834.07  5087.8 1833.92
  5120.9 1834.24  5173.7 1835.82  5247.8 1836.48  5270.6 1837.64  5296.8 1837.90
#Mann=3,-1,0
  4705.7    0.05       0  5011.2    0.05       0  5016.1    0.05       0
Bank Sta=5011.2,5016.1
Exp/Cntr=0.3,0.1

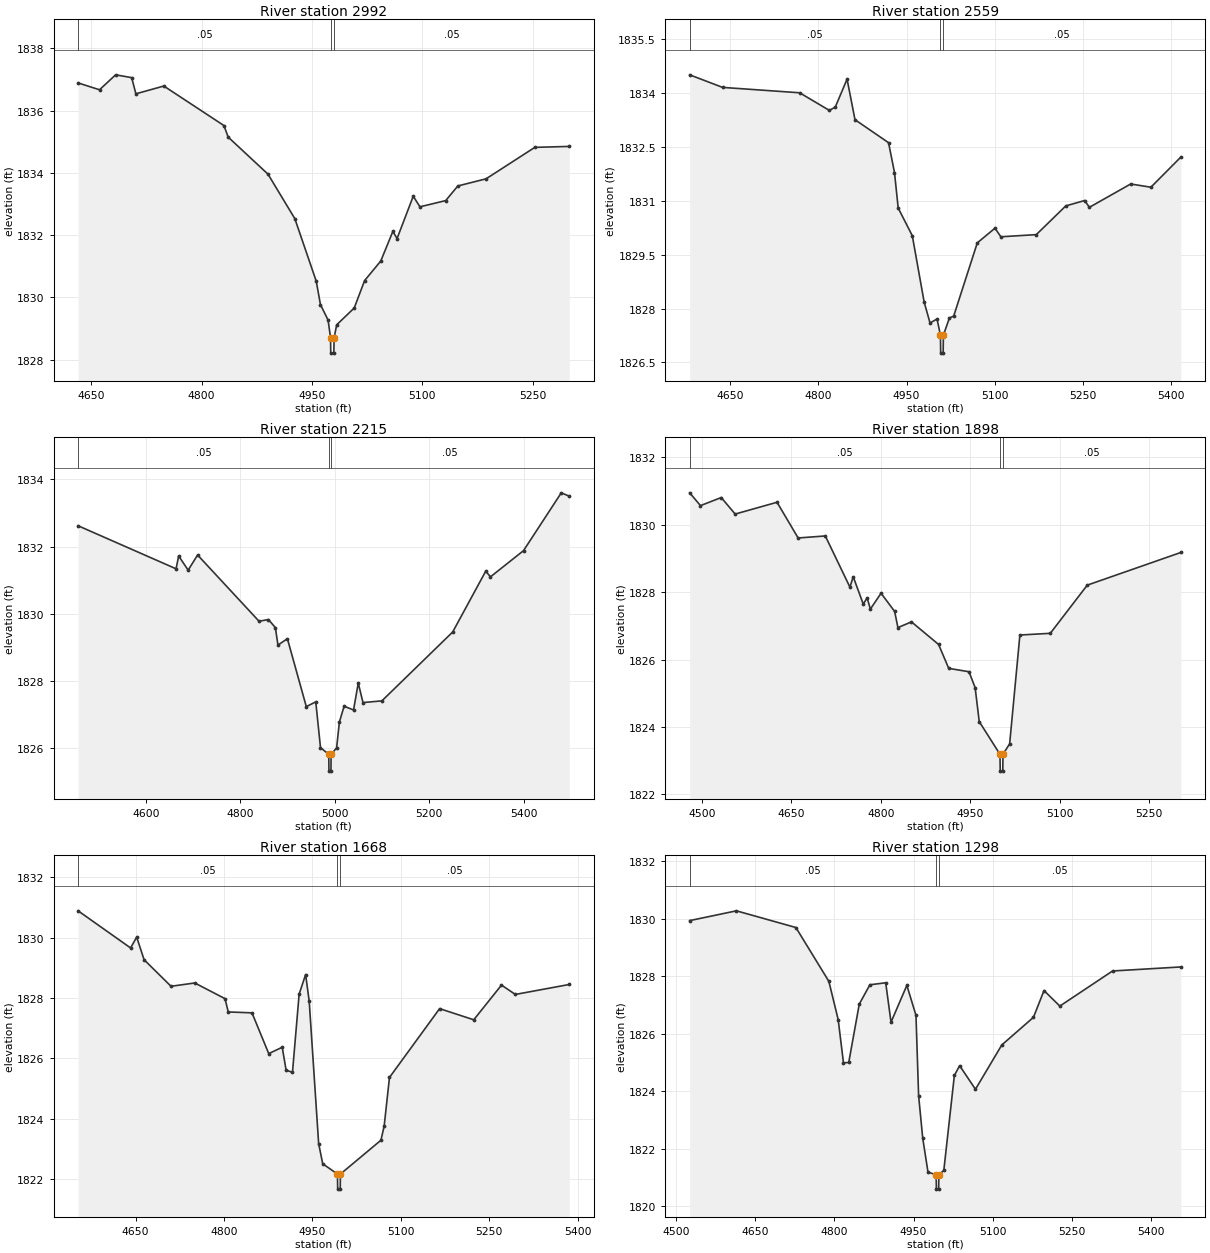
Type RM Length L Ch R = 1,2992,433,433,433
BEGIN DESCRIPTION:
Elm 01 89 2992.29
END DESCRIPTION:
XS GIS Cut Line= 3
      1611986.34      6802808.05      1612311.86      6802985.13
      1612574.70      6803123.06
#Sta/Elev= 30
  4632.2 1836.89  4661.3 1836.67  4683.2 1837.15  4705.0 1837.06  4710.7 1836.54
  4748.7 1836.79  4830.4 1835.52  4836.1 1835.15  4890.2 1833.96  4926.7 1832.53
  4955.8 1830.52  4961.5 1829.77  4971.9 1829.27  4975.2 1828.71  4975.5 1828.21
  4979.7 1828.21  4980.1 1828.71  4983.6 1829.12  5007.4 1829.66  5021.5 1830.54
  5043.5 1831.17  5059.9 1832.12  5065.6 1831.89  5087.6 1833.25  5096.7 1832.91
  5131.7 1833.11  5148.2 1833.58  5186.6 1833.81  5252.8 1834.82  5299.6 1834.85
#Mann=3,-1,0
  4632.2    0.05       0  4975.2    0.05       0  4980.1    0.05       0
Bank Sta=4975.2,4980.1
Exp/Cntr=0.3,0.1

Type RM Length L Ch R = 1,2559,344,344,344
BEGIN DESCRIPTION:
Elm 01 89 2558.53
END DESCRIPTION:
XS GIS Cut Line= 3
      1611689.47      6803266.38      1612103.52      6803321.07
      1612520.09      6803357.52
#Sta/Elev= 30
  4580.9 1834.51  4636.9 1834.16  4768.0 1834.01  4818.5 1833.52  4828.6 1833.61
  4848.7 1834.39  4862.2 1833.26  4919.3 1832.62  4929.4 1831.79  4935.7 1830.80
  4959.7 1830.03  4979.9 1828.18  4989.9 1827.60  5001.8 1827.71  5007.6 1827.26
  5008.0 1826.76  5012.2 1826.76  5012.6 1827.26  5022.9 1827.74  5030.1 1827.79
  5070.3 1829.83  5100.4 1830.24  5110.4 1830.00  5170.7 1830.06  5220.9 1830.86
  5253.1 1831.01  5261.0 1830.82  5331.3 1831.47  5365.7 1831.38  5416.7 1832.22
#Mann=3,-1,0
  4580.9    0.05       0  5007.6    0.05       0  5012.6    0.05       0
Bank Sta=5007.6,5012.6
Exp/Cntr=0.3,0.1

Type RM Length L Ch R = 1,2215,317,317,317
BEGIN DESCRIPTION:
Elm 01 89 2215.06
END DESCRIPTION:
XS GIS Cut Line= 3
      1611612.21      6803623.15      1612159.08      6803649.19
      1612651.89      6803649.19
#Sta/Elev= 30
  4456.4 1832.62  4663.9 1831.34  4669.4 1831.72  4689.5 1831.30  4709.5 1831.75
  4839.6 1829.78  4859.6 1829.83  4874.2 1829.59  4879.7 1829.07  4899.7 1829.26
  4939.7 1827.24  4959.8 1827.38  4969.8 1826.02  4987.3 1825.82  4987.7 1825.32
  4991.9 1825.32  4992.3 1825.82  5003.9 1826.01  5009.8 1826.78  5019.8 1827.25
  5039.8 1827.14  5049.8 1827.94  5059.8 1827.36  5099.8 1827.41  5249.8 1829.46
  5319.8 1831.27  5329.8 1831.10  5399.8 1831.88  5479.8 1833.60  5496.7 1833.50
#Mann=3,-1,0
  4456.4    0.05       0  4987.3    0.05       0  4992.3    0.05       0
Bank Sta=4987.3,4992.3
Exp/Cntr=0.3,0.1

Type RM Length L Ch R = 1,1898,230,230,230
BEGIN DESCRIPTION:
Mapping XS ca982fee
END DESCRIPTION:
XS GIS Cut Line= 4
      1611718.39      6803733.13      1612015.72      6803863.35
      1612354.26      6804023.94      1612477.94      6804039.13
#Sta/Elev= 30
  4479.3 1830.95  4497.4 1830.57  4532.2 1830.81  4555.6 1830.32  4625.8 1830.67
  4661.2 1829.61  4706.8 1829.67  4748.1 1828.15  4753.6 1828.46  4770.4 1827.65
  4777.0 1827.83  4782.4 1827.50  4800.3 1827.97  4823.1 1827.43  4828.6 1826.95
  4851.3 1827.12  4896.8 1826.45  4913.8 1825.74  4947.8 1825.64  4958.1 1825.17
  4965.0 1824.16  4999.8 1823.19  5000.2 1822.69  5004.5 1822.69  5004.8 1823.19
  5016.0 1823.50  5033.2 1826.73  5084.2 1826.78  5146.2 1828.21  5303.2 1829.18
#Mann=3,-1,0
  4479.3    0.05       0  4999.8    0.05       0  5004.8    0.05       0
Bank Sta=4999.8,5004.8
Exp/Cntr=0.3,0.1

Type RM Length L Ch R = 1,1668,370,370,370
BEGIN DESCRIPTION:
Elm 01 89 1667.75
END DESCRIPTION:
XS GIS Cut Line= 3
      1611594.83      6803857.52      1611998.49      6804045.03
      1612355.23      6804198.66
#Sta/Elev= 30
  4552.5 1830.89  4641.6 1829.66  4651.9 1830.02  4664.5 1829.27  4710.2 1828.39
  4750.5 1828.50  4801.8 1827.98  4807.3 1827.54  4847.6 1827.51  4876.0 1826.16
  4898.9 1826.37  4905.5 1825.61  4916.3 1825.54  4927.6 1828.13  4938.6 1828.78
  4944.7 1827.89  4960.7 1823.18  4967.6 1822.51  4992.6 1822.17  4993.0 1821.67
  4997.3 1821.67  4997.7 1822.17  5066.4 1823.29  5071.9 1823.76  5080.9 1825.37
  5166.0 1827.65  5223.9 1827.28  5271.0 1828.43  5294.5 1828.12  5386.0 1828.45
#Mann=3,-1,0
  4552.5    0.05       0  4992.6    0.05       0  4997.7    0.05       0
Bank Sta=4992.6,4997.7
Exp/Cntr=0.3,0.1

Type RM Length L Ch R = 1,1298,297,297,297
BEGIN DESCRIPTION:
Elm 01 89 1297.85
END DESCRIPTION:
XS GIS Cut Line= 3
      1611263.91      6804277.66      1611736.12      6804305.44
      1612194.48      6804308.91
#Sta/Elev= 30
  4525.5 1829.93  4614.1 1830.27  4726.9 1829.69  4789.4 1827.82  4807.1 1826.49
  4817.1 1824.99  4827.1 1825.00  4847.1 1827.03  4867.2 1827.70  4897.2 1827.77
  4907.3 1826.40  4937.3 1827.68  4954.6 1826.64  4959.6 1823.85  4967.4 1822.37
  4977.4 1821.19  4992.9 1821.10  4993.3 1820.60  4997.6 1820.60  4998.0 1821.10
  5007.4 1821.25  5027.4 1824.55  5037.4 1824.89  5067.4 1824.07  5117.4 1825.61
  5177.4 1826.57  5197.4 1827.50  5227.4 1826.96  5327.4 1828.18  5456.9 1828.32
#Mann=3,-1,0
  4525.5    0.05       0  4992.9    0.03       0  4998.0    0.05       0
Bank Sta=4992.9,4998
Exp/Cntr=0.3,0.1

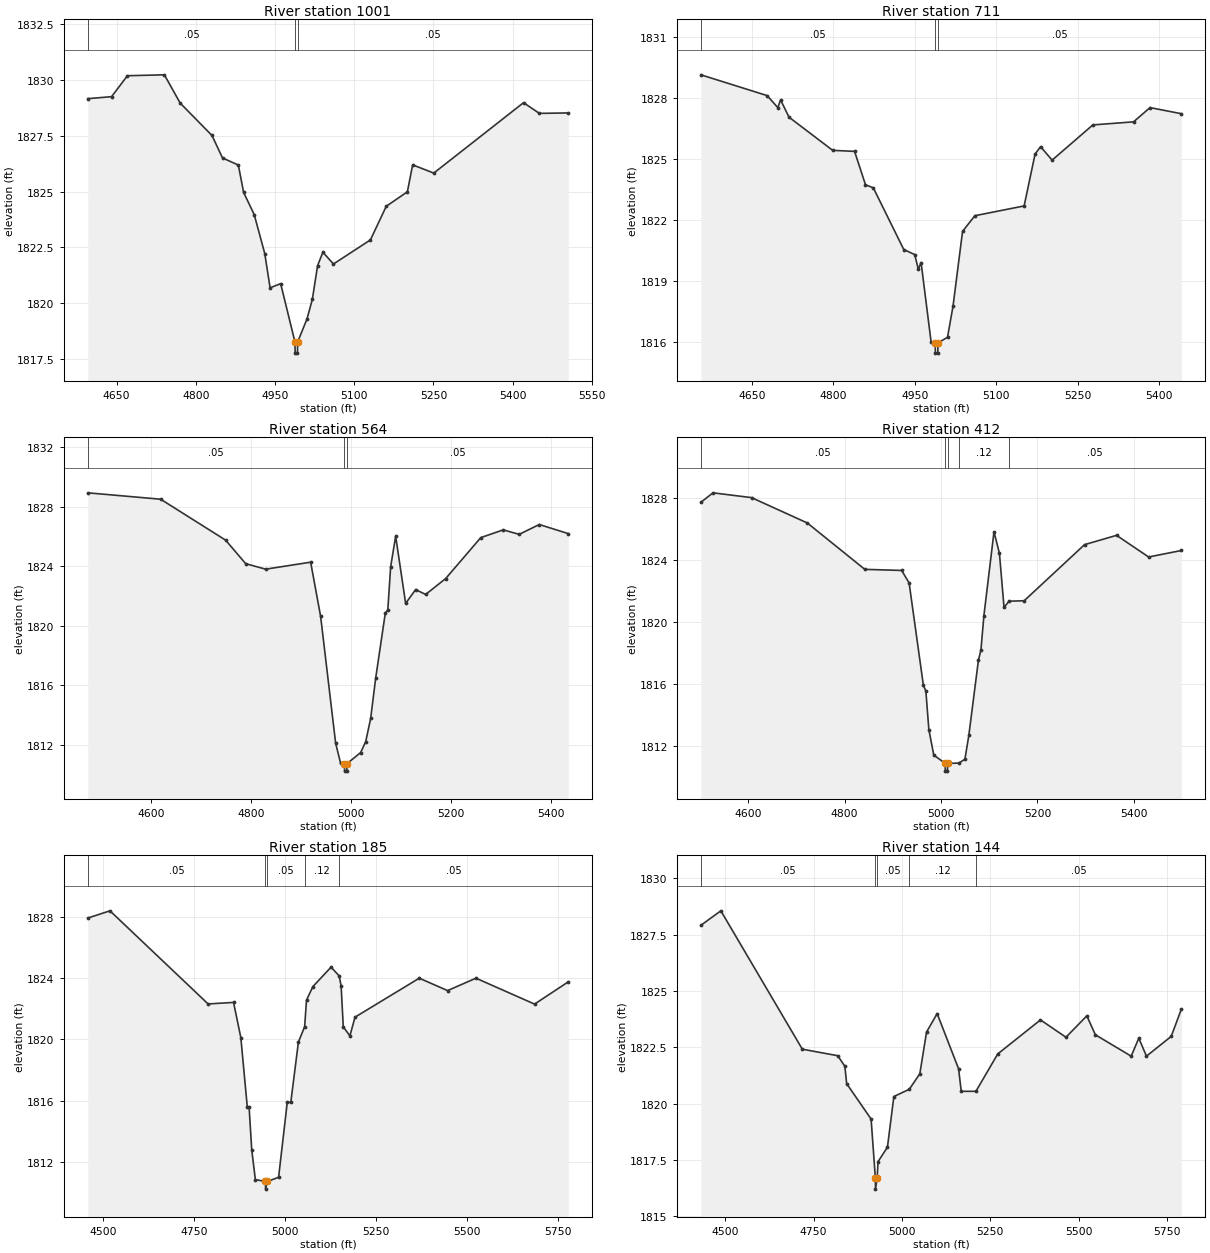
Type RM Length L Ch R = 1,1001,290,290,290
BEGIN DESCRIPTION:
Elm 01 89 1001.22
END DESCRIPTION:
XS GIS Cut Line= 3
      1611250.06      6804527.66      1611649.31      6804513.78
      1612159.70      6804510.30
#Sta/Elev= 30
  4595.4 1829.17  4640.4 1829.26  4670.4 1830.20  4740.4 1830.24  4770.4 1828.97
  4830.5 1827.52  4850.5 1826.51  4880.5 1826.19  4890.5 1824.96  4910.5 1823.97
  4930.5 1822.22  4940.6 1820.68  4960.6 1820.87  4987.7 1818.25  4988.1 1817.75
  4992.4 1817.75  4992.8 1818.25  5010.6 1819.29  5020.6 1820.16  5030.6 1821.68
  5040.6 1822.28  5060.6 1821.75  5130.6 1822.83  5160.6 1824.34  5200.6 1824.99
  5210.6 1826.20  5250.6 1825.83  5420.6 1828.99  5450.6 1828.51  5505.3 1828.53
#Mann=3,-1,0
  4595.4    0.05       0  4987.7    0.05       0  4992.8    0.05       0
Bank Sta=4987.7,4992.8
Exp/Cntr=0.3,0.1

Type RM Length L Ch R = 1,711,147,147,147
BEGIN DESCRIPTION:
Elm 01 89 711.25
END DESCRIPTION:
XS GIS Cut Line= 3
      1611263.95      6804840.16      1611704.87      6804788.08
      1612142.37      6804732.53
#Sta/Elev= 30
  4556.2 1829.12  4678.1 1828.10  4697.8 1827.51  4702.9 1827.89  4718.4 1827.04
  4798.9 1825.41  4839.2 1825.36  4859.3 1823.72  4873.7 1823.57  4929.8 1820.54
  4950.0 1820.29  4956.6 1819.57  4961.7 1819.90  4980.2 1815.99  4987.7 1815.95
  4988.1 1815.45  4992.5 1815.45  4992.8 1815.95  5010.4 1816.23  5020.5 1817.75
  5038.1 1821.43  5060.8 1822.20  5151.5 1822.68  5171.7 1825.23  5181.8 1825.59
  5203.1 1824.93  5278.1 1826.66  5353.1 1826.81  5383.4 1827.51  5441.2 1827.21
#Mann=3,-1,0
  4556.2    0.05       0  4987.7    0.05       0  4992.8    0.05       0
Bank Sta=4987.7,4992.8
Exp/Cntr=0.3,0.1

Type RM Length L Ch R = 1,564,152,152,152
BEGIN DESCRIPTION:
Mapping XS 724b0465
END DESCRIPTION:
XS GIS Cut Line= 3
      1611179.30      6804951.89      1611922.83      6804928.45
      1612127.28      6804854.23
#Sta/Elev= 30
  4473.5 1828.94  4619.3 1828.51  4749.3 1825.76  4789.4 1824.18  4829.4 1823.81
  4919.4 1824.28  4939.4 1820.63  4969.4 1812.12  4979.4 1810.76  4986.9 1810.74
  4987.3 1810.24  4991.7 1810.24  4992.1 1810.74  5019.5 1811.49  5029.5 1812.21
  5039.5 1813.78  5049.5 1816.48  5068.8 1820.86  5073.8 1821.08  5079.5 1823.97
  5089.5 1826.03  5109.5 1821.51  5129.5 1822.44  5149.5 1822.11  5189.6 1823.18
  5259.8 1825.93  5304.8 1826.45  5336.7 1826.15  5376.9 1826.81  5434.9 1826.20
#Mann=3,-1,0
  4473.5    0.05       0  4986.9    0.05       0  4992.1    0.05       0
Bank Sta=4986.9,4992.1
Exp/Cntr=0.3,0.1

Type RM Length L Ch R = 1,412,227,227,227
BEGIN DESCRIPTION:
Elm 01 89 412.38
END DESCRIPTION:
XS GIS Cut Line= 3
      1611222.26      6805187.38      1611708.34      6805086.69
      1612187.54      6804944.32
#Sta/Elev= 30
  4502.1 1827.75  4527.1 1828.36  4607.0 1828.05  4722.7 1826.41  4841.9 1823.41
  4918.3 1823.34  4933.8 1822.53  4963.4 1815.90  4968.5 1815.55  4974.7 1813.05
  4984.9 1811.40  5008.5 1810.86  5008.9 1810.36  5013.3 1810.36  5013.7 1810.86
  5036.9 1810.88  5049.5 1811.13  5057.6 1812.67  5077.5 1817.53  5082.7 1818.19
  5088.9 1820.42  5109.8 1825.84  5121.1 1824.44  5130.6 1820.95  5141.0 1821.35
  5172.4 1821.38  5297.6 1825.01  5364.0 1825.61  5430.4 1824.21  5498.4 1824.63
#Mann=5,-1,0
  4502.1    0.05       0  5008.5    0.05       0  5013.7    0.05       0
  5036.9    0.12       0  5141.0    0.05       0
Bank Sta=5008.5,5013.7
Exp/Cntr=0.3,0.1

Type RM Length L Ch R = 1,185,41,41,41
BEGIN DESCRIPTION:
Mapping XS 192b7d4f
END DESCRIPTION:
XS GIS Cut Line= 6
      1611264.01      6805280.01      1611743.15      6805282.62
      1611812.16      6805266.99      1611839.50      6805235.74
      1611846.01      6805134.18      1612429.39      6804899.79
#Sta/Elev= 30
  4456.9 1827.90  4517.9 1828.37  4787.9 1822.30  4857.9 1822.40  4877.9 1820.11
  4895.6 1815.60  4900.6 1815.60  4907.9 1812.79  4917.9 1810.85  4945.6 1810.73
  4946.0 1810.23  4950.8 1810.73  4981.8 1811.00  5005.7 1815.89  5015.4 1815.89
  5036.3 1819.81  5053.5 1820.82  5058.6 1822.55  5076.1 1823.43  5126.2 1824.70
  5148.4 1824.13  5153.8 1823.49  5159.8 1820.81  5178.0 1820.22  5192.1 1821.44
  5368.9 1823.98  5446.8 1823.17  5524.8 1823.98  5686.1 1822.29  5778.8 1823.74
#Mann=5,-1,0
  4456.9    0.05       0  4945.6    0.05       0  4950.8    0.05       0
  5053.5    0.12       0  5148.4    0.05       0
Bank Sta=4945.6,4950.8
Exp/Cntr=0.3,0.1

Type RM Length L Ch R = 1,144,71,71,71
BEGIN DESCRIPTION:
Mapping XS 84a10447
END DESCRIPTION:
XS GIS Cut Line= 6
      1611258.78      6805300.85      1611670.23      6805325.59
      1611793.93      6805317.77      1611855.13      6805266.99
      1611856.43      6805157.62      1612436.64      6804912.26
#Sta/Elev= 30
  4431.5 1827.92  4487.8 1828.56  4718.2 1822.42  4818.4 1822.13  4838.5 1821.66
  4843.6 1820.89  4912.7 1819.32  4924.7 1816.71  4925.1 1816.21  4929.9 1816.71
  4932.3 1817.43  4958.9 1818.07  4977.1 1820.32  5020.7 1820.64  5050.5 1821.33
  5069.5 1823.18  5099.5 1824.00  5160.1 1821.55  5167.6 1820.55  5209.1 1820.55
  5270.9 1822.21  5391.7 1823.72  5463.7 1822.95  5522.8 1823.90  5546.9 1823.06
  5648.2 1822.11  5669.8 1822.91  5691.4 1822.11  5761.5 1822.99  5790.2 1824.20
#Mann=5,-1,0
  4431.5    0.05       0  4924.7    0.05       0  4929.9    0.05       0
  5020.7    0.12       0  5209.1    0.05       0
Bank Sta=4924.7,4929.9
Exp/Cntr=0.3,0.1

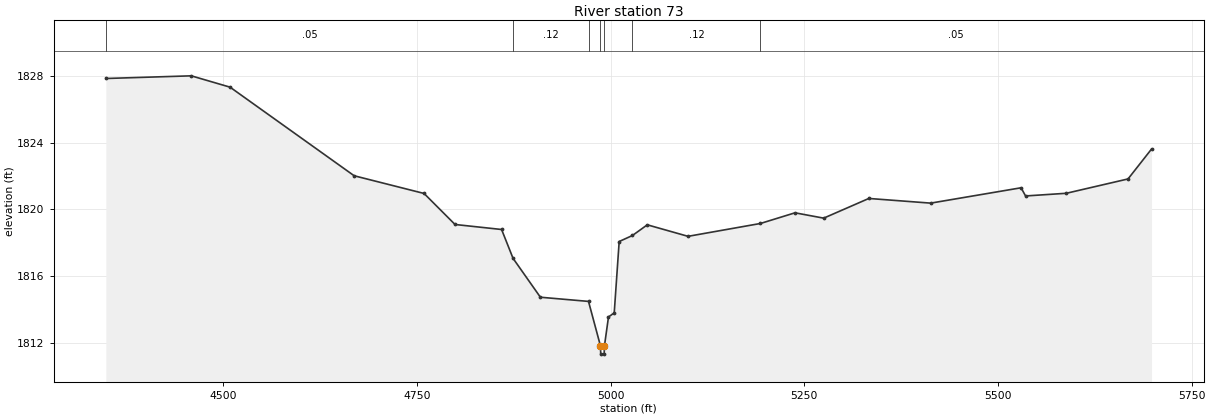
Type RM Length L Ch R = 1,73,0,0,0
BEGIN DESCRIPTION:
Elm 01 89 502.286
END DESCRIPTION:
XS GIS Cut Line= 3
      1611204.83      6805329.75      1611855.57      6805365.03
      1612454.88      6805006.82
#Sta/Elev= 30
  4348.3 1827.85  4458.6 1828.01  4508.7 1827.33  4668.9 1822.02  4759.1 1820.96
  4799.1 1819.10  4859.2 1818.80  4874.0 1817.07  4909.3 1814.74  4971.4 1814.49
  4986.8 1811.83  4987.2 1811.33  4991.6 1811.33  4992.0 1811.83  4997.2 1813.56
  5004.6 1813.80  5011.0 1818.08  5028.1 1818.44  5047.3 1819.08  5099.9 1818.39
  5193.3 1819.16  5238.0 1819.80  5275.0 1819.48  5333.3 1820.66  5413.1 1820.38
  5529.8 1821.30  5535.6 1820.81  5588.2 1820.97  5667.9 1821.83  5698.2 1823.62
#Mann=7,-1,0
  4348.3    0.05       0  4874.0    0.12       0  4971.4    0.05       0
  4986.8    0.05       0  4992.0    0.05       0  5028.1    0.12       0
  5193.3    0.05       0
Bank Sta=4986.8,4992
Exp/Cntr=0.3,0.1

Chan Stop Cuts=-1