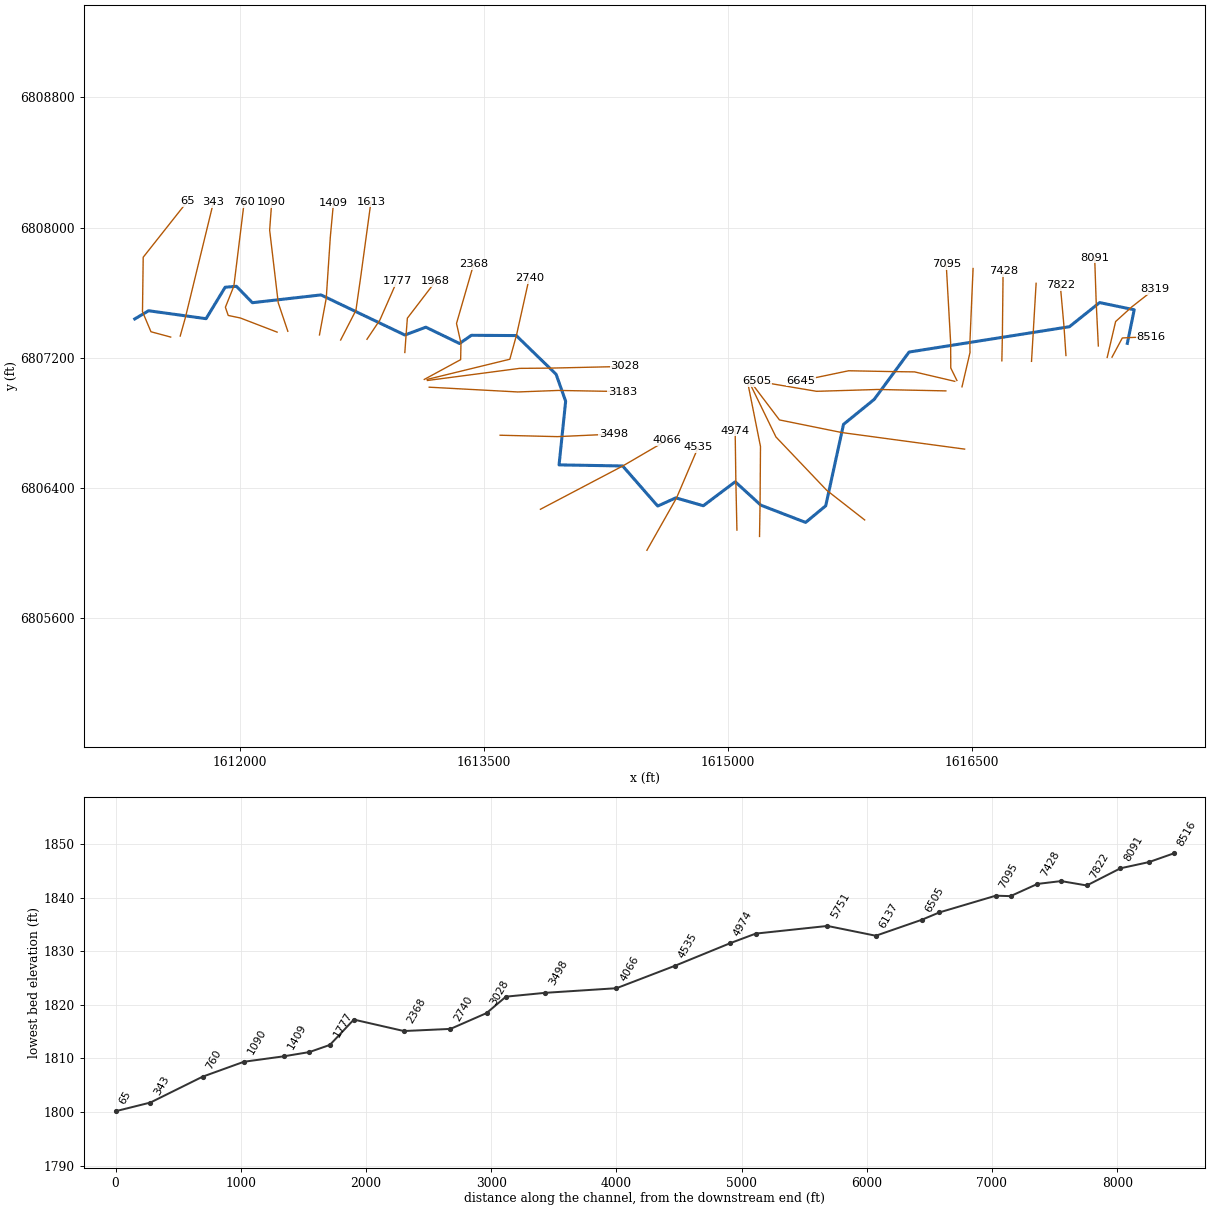
--- Elm 01 90.prj (project) ---

Proj Title=Elm 01 90 Base Level Engineering
Current Plan=p01
Default Exp/Contr=0.3,0.1
English Units
Geom File=g01
Flow File=f01
Plan File=p01
BEGIN DESCRIPTION:
Elm 01 90
END DESCRIPTION:

--- Elm 01 90.p01 (plan) ---

Plan Title=Multiple Run
Short Identifier=Multiple
Geom File=g01
Flow File=f01
Subcritical Flow
K Sum by GR= 0
Std Step Tol= 0.01
Critical Tol= 0.01
Num of Std Step Trials= 20
Max Error Tol= 0.3
Flow Tol Ratio= 0.001
Split Flow NTrial= 30
Split Flow Tol= 0.02
Split Flow Ratio= 0.02
Log Output Level= 0
Friction Slope Method= 1
Unsteady Friction Slope Method= 2
Unsteady Bridges Friction Slope Method= 1
Parabolic Critical Depth
Global Vel Dist=  1 , 1 , 1
Global Log Level= 0
CheckData=True
Encroach Param= -1, 0, 0, 0
BEGIN DESCRIPTION:
Multiple Run
END DESCRIPTION:

--- Elm 01 90.f01 (steady flow) ---

Flow Title=Multiple
Number of Profiles=7
Profile Names=10-year,25-year,50-year,1pct_min,100-year,1pct_plu,500-year
River Rch & RM= Elm 01 90,Reach-1,8516
     173     234     283     213     341     470     502
River Rch & RM= Elm 01 90,Reach-1,8091
     316     443     548     420     673     926    1030
Boundary for River Rch & Prof#=Elm 01 90,Reach-1,1
Up Type=0
Dn Type=3
Dn Slope=0.001
Boundary for River Rch & Prof#=Elm 01 90,Reach-1,2
Up Type=0
Dn Type=3
Dn Slope=0.001
Boundary for River Rch & Prof#=Elm 01 90,Reach-1,3
Up Type=0
Dn Type=3
Dn Slope=0.001
Boundary for River Rch & Prof#=Elm 01 90,Reach-1,4
Up Type=0
Dn Type=3
Dn Slope=0.001
Boundary for River Rch & Prof#=Elm 01 90,Reach-1,5
Up Type=0
Dn Type=3
Dn Slope=0.001
Boundary for River Rch & Prof#=Elm 01 90,Reach-1,6
Up Type=0
Dn Type=3
Dn Slope=0.001
Boundary for River Rch & Prof#=Elm 01 90,Reach-1,7
Up Type=0
Dn Type=3
Dn Slope=0.001

--- Elm 01 90.g01 (geometry) ---

Geom Title=Existing Conditions

River Reach=Elm 01 90,Reach-1
Reach XY= 30
      1617455.00      6807288.00      1617497.33      6807494.52
      1617284.57      6807538.53      1617099.07      6807390.25
      1616113.47      6807234.51      1615899.38      6806943.62
      1615710.83      6806790.30      1615601.39      6806289.48
      1615477.84      6806187.52      1615202.57      6806293.52
      1615045.20      6806437.30      1614849.11      6806289.96
      1614680.00      6806338.39      1614568.91      6806288.05
      1614353.54      6806534.46      1613962.61      6806541.07
      1614003.06      6806932.29      1613944.48      6807097.79
      1613699.56      6807335.83      1613423.68      6807337.49
      1613350.74      6807287.09      1613143.96      6807387.34
      1613014.80      6807339.22      1612499.48      6807585.66
      1612077.68      6807537.83      1611979.93      6807638.61
      1611910.47      6807632.90      1611793.17      6807439.61
      1611439.83      6807488.41      1611355.00      6807438.00

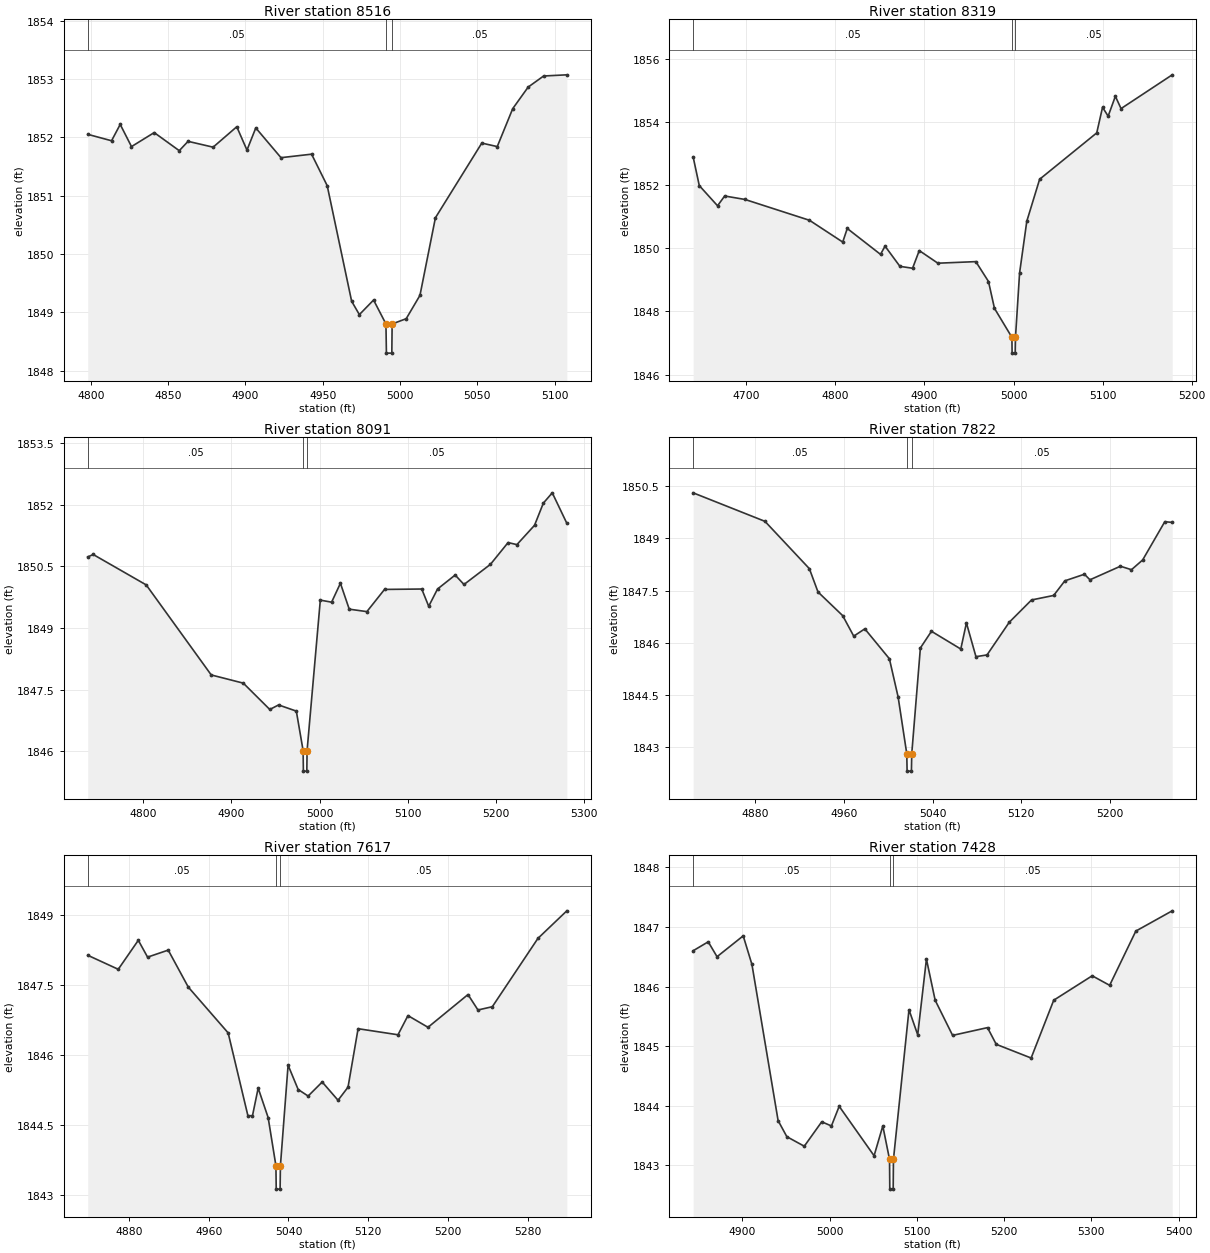
Type RM Length L Ch R = 1,8516,197,197,197
BEGIN DESCRIPTION:
Elm 01 90 8516.255
END DESCRIPTION:
XS GIS Cut Line= 4
      1617360.79      6807203.07      1617424.22      6807321.16
      1617492.09      6807324.50      1617599.96      6807327.02
#Sta/Elev= 30
  4798.0 1852.05  4813.4 1851.94  4819.0 1852.22  4826.3 1851.84  4841.0 1852.08
  4857.2 1851.77  4862.9 1851.93  4879.1 1851.83  4894.4 1852.18  4901.0 1851.78
  4906.7 1852.16  4923.0 1851.65  4942.8 1851.71  4952.9 1851.17  4968.7 1849.19
  4973.7 1848.96  4982.9 1849.21  4990.9 1848.80  4991.2 1848.30  4994.7 1848.30
  4994.9 1848.80  5004.0 1848.89  5012.9 1849.29  5022.9 1850.62  5052.9 1851.90
  5062.9 1851.84  5072.9 1852.49  5082.9 1852.86  5092.9 1853.05  5107.9 1853.07
#Mann=3,-1,0
  4798.0    0.05       0  4990.9    0.05       0  4994.9    0.05       0
Bank Sta=4990.9,4994.9
Exp/Cntr=0.3,0.1

Type RM Length L Ch R = 1,8319,228,228,228
BEGIN DESCRIPTION:
Elm 01 90 8318.82
END DESCRIPTION:
XS GIS Cut Line= 4
      1617331.26      6807201.31      1617383.02      6807421.96
      1617481.65      6807511.40      1617621.58      6807621.28
#Sta/Elev= 30
  4640.4 1852.90  4647.3 1851.99  4667.8 1851.35  4675.8 1851.66  4698.6 1851.55
  4771.0 1850.89  4808.3 1850.20  4813.4 1850.63  4850.7 1849.81  4855.8 1850.07
  4872.5 1849.43  4886.7 1849.37  4894.2 1849.93  4915.1 1849.53  4957.7 1849.58
  4971.9 1848.95  4978.6 1848.10  4998.2 1847.18  4998.4 1846.68  5001.9 1846.68
  5002.2 1847.18  5006.8 1849.22  5014.9 1850.86  5029.3 1852.19  5093.4 1853.66
  5099.9 1854.47  5106.2 1854.19  5114.3 1854.82  5120.7 1854.43  5178.1 1855.50
#Mann=3,-1,0
  4640.4    0.05       0  4998.2    0.05       0  5002.2    0.05       0
Bank Sta=4998.2,5002.2
Exp/Cntr=0.3,0.1

Type RM Length L Ch R = 1,8091,269,269,269
BEGIN DESCRIPTION:
Elm 01 90 8091.47
END DESCRIPTION:
XS GIS Cut Line= 3
      1617276.79      6807271.82      1617263.77      6807537.44
      1617254.27      6807814.54
#Sta/Elev= 30
  4737.2 1850.73  4743.4 1850.79  4803.5 1850.05  4877.2 1847.86  4913.6 1847.66
  4943.6 1847.02  4953.6 1847.13  4973.7 1846.98  4981.4 1846.02  4981.7 1845.52
  4985.6 1845.52  4985.9 1846.02  5000.9 1849.68  5013.7 1849.63  5023.7 1850.09
  5033.7 1849.46  5053.7 1849.40  5073.7 1849.94  5115.9 1849.95  5123.8 1849.53
  5133.8 1849.95  5153.8 1850.29  5163.8 1850.06  5193.8 1850.55  5213.8 1851.08
  5223.8 1851.03  5243.8 1851.50  5253.8 1852.04  5263.9 1852.29  5280.4 1851.55
#Mann=3,-1,0
  4737.2    0.05       0  4981.4    0.05       0  4985.9    0.05       0
Bank Sta=4981.4,4985.9
Exp/Cntr=0.3,0.1

Type RM Length L Ch R = 1,7822,205,205,205
BEGIN DESCRIPTION:
Elm 01 90 7822.37
END DESCRIPTION:
XS GIS Cut Line= 3
      1617077.78      6807213.24      1617065.85      6807390.10
      1617043.20      6807644.63
#Sta/Elev= 30
  4823.7 1850.31  4888.6 1849.49  4928.7 1848.13  4936.5 1847.46  4958.8 1846.78
  4968.8 1846.19  4978.8 1846.40  5001.0 1845.54  5008.9 1844.44  5016.7 1842.81
  5017.0 1842.31  5020.9 1842.31  5021.2 1842.81  5029.0 1845.85  5039.0 1846.33
  5065.5 1845.82  5070.6 1846.57  5079.2 1845.60  5089.2 1845.65  5109.3 1846.59
  5129.4 1847.23  5149.4 1847.36  5159.5 1847.78  5177.2 1847.97  5182.2 1847.81
  5209.7 1848.20  5219.7 1848.10  5229.8 1848.38  5249.8 1849.48  5256.5 1849.46
#Mann=3,-1,0
  4823.7    0.05       0  5016.7    0.05       0  5021.2    0.05       0
Bank Sta=5016.7,5021.2
Exp/Cntr=0.3,0.1

Type RM Length L Ch R = 1,7617,189,189,189
BEGIN DESCRIPTION:
Elm 01 90 7616.67
END DESCRIPTION:
XS GIS Cut Line= 3
      1616866.20      6807177.41      1616875.96      6807342.36
      1616894.41      6807656.98
#Sta/Elev= 30
  4838.7 1848.13  4869.3 1847.83  4889.4 1848.45  4898.7 1848.09  4919.4 1848.24
  4939.5 1847.45  4979.5 1846.47  4999.3 1844.70  5003.9 1844.70  5009.6 1845.29
  5019.6 1844.66  5027.4 1843.63  5027.7 1843.13  5031.6 1843.13  5031.9 1843.63
  5039.6 1845.78  5049.7 1845.26  5059.7 1845.12  5073.8 1845.42  5089.7 1845.03
  5099.7 1845.31  5109.8 1846.56  5149.8 1846.43  5159.8 1846.84  5179.9 1846.59
  5220.0 1847.29  5230.0 1846.96  5244.4 1847.03  5290.1 1848.49  5319.1 1849.08
#Mann=3,-1,0
  4838.7    0.05       0  5027.4    0.05       0  5031.9    0.05       0
Bank Sta=5027.4,5031.9
Exp/Cntr=0.3,0.1

Type RM Length L Ch R = 1,7428,215,215,215
BEGIN DESCRIPTION:
Elm 01 90 7428.05
END DESCRIPTION:
XS GIS Cut Line= 3
      1616683.90      6807180.65      1616687.16      6807339.10
      1616691.50      6807729.70
#Sta/Elev= 30
  4843.5 1846.60  4860.8 1846.75  4870.9 1846.50  4900.9 1846.85  4910.9 1846.37
  4940.9 1843.75  4950.9 1843.48  4970.9 1843.32  4990.9 1843.73  5002.0 1843.66
  5010.9 1843.99  5050.9 1843.16  5060.9 1843.66  5068.6 1843.10  5068.9 1842.60
  5072.8 1842.60  5073.1 1843.10  5090.9 1845.61  5100.9 1845.19  5110.9 1846.46
  5120.9 1845.77  5140.9 1845.18  5180.9 1845.31  5190.9 1845.03  5230.9 1844.80
  5256.8 1845.77  5300.9 1846.18  5320.9 1846.02  5350.9 1846.93  5392.6 1847.27
#Mann=3,-1,0
  4843.5    0.05       0  5068.6    0.05       0  5073.1    0.05       0
Bank Sta=5068.6,5073.1
Exp/Cntr=0.3,0.1

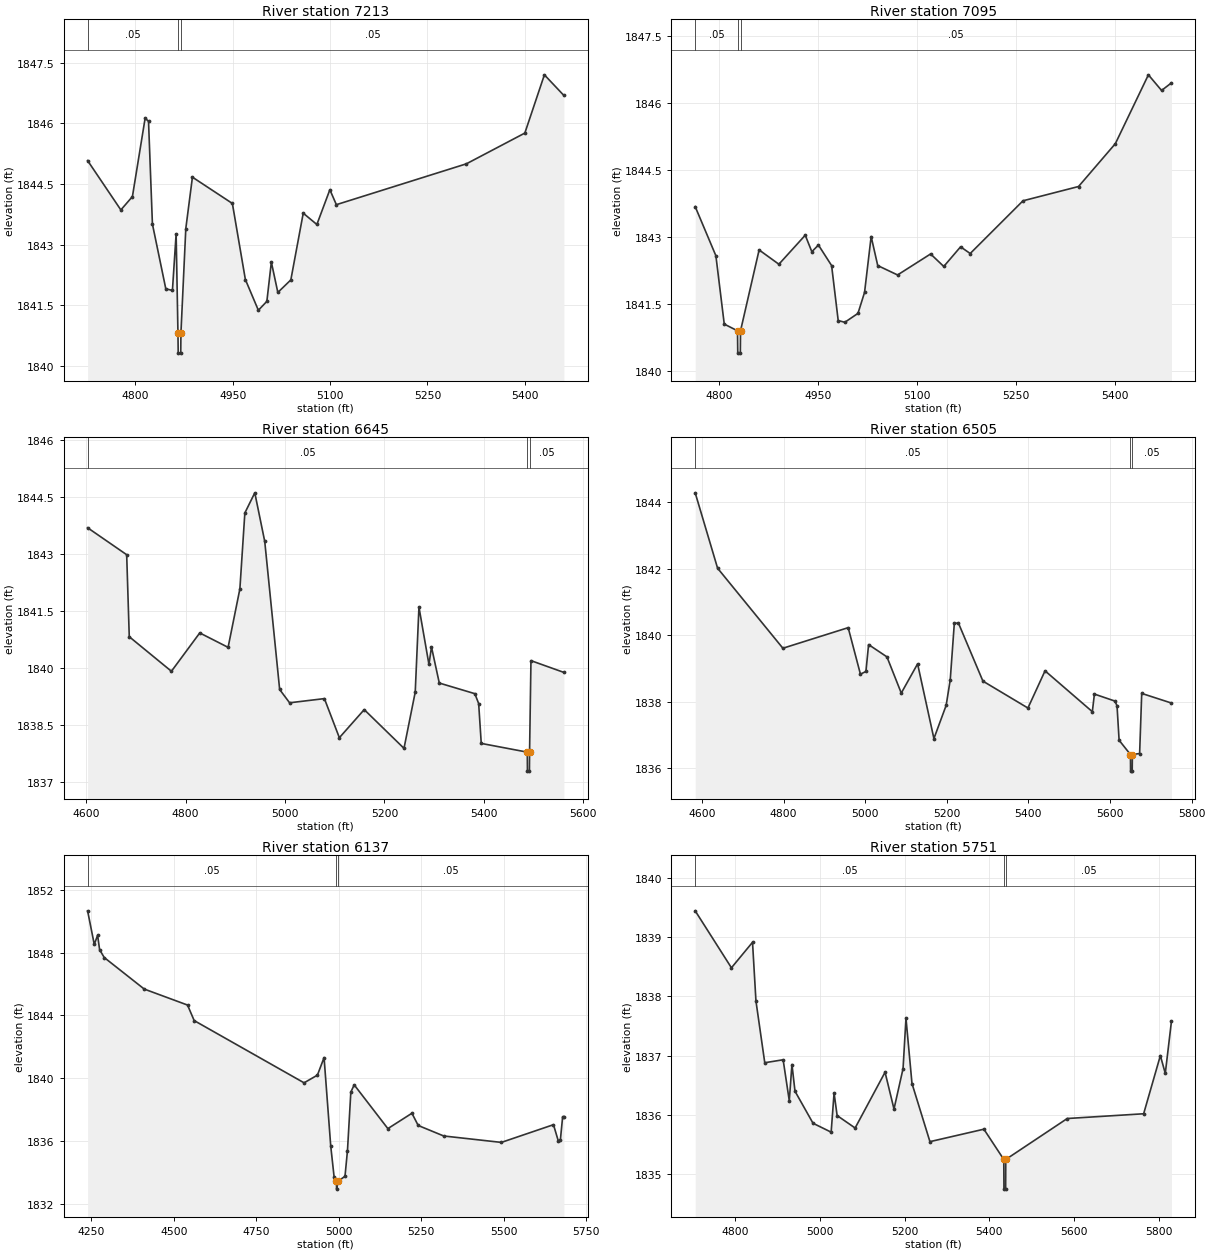
Type RM Length L Ch R = 1,7213,118,118,118
BEGIN DESCRIPTION:
Elm 01 90 7212.83
END DESCRIPTION:
XS GIS Cut Line= 4
      1616438.91      6807020.78      1616488.12      6807231.69
      1616487.43      6807291.14      1616506.97      6807748.00
#Sta/Elev= 30
  4726.7 1845.08  4777.9 1843.86  4795.7 1844.19  4815.3 1846.13  4820.5 1846.05
  4826.5 1843.51  4847.1 1841.91  4857.3 1841.87  4863.0 1843.27  4865.8 1840.82
  4866.2 1840.32  4870.1 1840.32  4870.4 1840.82  4877.9 1843.40  4888.1 1844.67
  4949.6 1844.02  4969.6 1842.14  4989.6 1841.38  5002.7 1841.60  5009.6 1842.57
  5019.6 1841.82  5039.6 1842.13  5058.7 1843.78  5079.7 1843.50  5099.7 1844.36
  5109.7 1843.99  5309.9 1845.00  5399.9 1845.76  5430.0 1847.20  5460.0 1846.69
#Mann=3,-1,0
  4726.7    0.05       0  4865.8    0.03       0  4870.4    0.05       0
Bank Sta=4865.8,4870.4
Exp/Cntr=0.3,0.1

Type RM Length L Ch R = 1,7095,450,450,450
BEGIN DESCRIPTION:
Elm 01 90 7094.2
END DESCRIPTION:
XS GIS Cut Line= 4
      1616407.65      6807059.80      1616369.89      6807136.63
      1616369.16      6807291.14      1616342.03      6807772.96
#Sta/Elev= 30
  4763.2 1843.68  4794.6 1842.58  4807.3 1841.05  4827.4 1840.90  4827.8 1840.40
  4831.7 1840.40  4832.0 1840.90  4860.2 1842.71  4890.2 1842.39  4930.2 1843.04
  4940.2 1842.67  4950.2 1842.82  4970.2 1842.36  4980.2 1841.13  4990.2 1841.09
  5010.2 1841.29  5020.2 1841.76  5030.2 1843.01  5040.2 1842.36  5070.3 1842.15
  5120.4 1842.62  5140.4 1842.34  5165.9 1842.78  5180.5 1842.63  5260.6 1843.81
  5344.9 1844.13  5400.8 1845.09  5450.9 1846.63  5470.9 1846.28  5485.9 1846.45
#Mann=3,-1,0
  4763.2    0.05       0  4827.4    0.03       0  4832.0    0.05       0
Bank Sta=4827.4,4832
Exp/Cntr=0.3,0.1

Type RM Length L Ch R = 1,6645,140,140,140
BEGIN DESCRIPTION:
Elm 01 90 6615.988
END DESCRIPTION:
XS GIS Cut Line= 5
      1616394.61      6807054.60      1616147.22      6807112.60
      1616004.33      6807114.51      1615742.33      6807119.57
      1615449.67      6807058.57
#Sta/Elev= 30
  4603.0 1843.69  4681.6 1842.98  4686.8 1840.82  4771.6 1839.91  4828.6 1840.92
  4885.6 1840.54  4909.3 1842.08  4919.3 1844.08  4939.3 1844.61  4959.3 1843.33
  4989.3 1839.43  5009.3 1839.08  5079.3 1839.19  5109.4 1838.16  5159.4 1838.90
  5239.4 1837.88  5262.0 1839.36  5269.5 1841.60  5289.6 1840.09  5294.7 1840.55
  5310.4 1839.60  5381.9 1839.32  5389.6 1839.06  5394.8 1838.01  5487.4 1837.78
  5487.7 1837.28  5491.7 1837.28  5492.0 1837.78  5494.8 1840.19  5561.0 1839.88
#Mann=3,-1,0
  4603.0    0.05       0  5487.4    0.03       0  5492.0    0.05       0
Bank Sta=5487.4,5492
Exp/Cntr=0.3,0.1

Type RM Length L Ch R = 1,6505,368,368,368
BEGIN DESCRIPTION:
Elm 01 90 6504.9
END DESCRIPTION:
XS GIS Cut Line= 4
      1616339.85      6806995.87      1615921.50      6807004.55
      1615545.34      6806993.22      1615178.20      6807055.14
#Sta/Elev= 30
  4583.4 1844.29  4638.3 1842.02  4798.3 1839.61  4958.3 1840.23  4988.3 1838.83
  5001.8 1838.91  5008.3 1839.72  5053.3 1839.35  5088.4 1838.26  5128.4 1839.14
  5168.4 1836.89  5198.4 1837.89  5208.4 1838.66  5218.4 1840.36  5228.4 1840.37
  5288.5 1838.62  5398.8 1837.81  5440.7 1838.93  5556.6 1837.70  5561.7 1838.23
  5611.8 1838.02  5617.1 1837.88  5622.2 1836.84  5650.0 1836.41  5650.3 1835.91
  5654.3 1835.91  5654.7 1836.41  5672.5 1836.44  5677.6 1838.25  5750.5 1837.96
#Mann=3,-1,0
  4583.4    0.05       0  5650.0    0.05       0  5654.7    0.05       0
Bank Sta=5650,5654.7
Exp/Cntr=0.3,0.1

Type RM Length L Ch R = 1,6137,386,386,386
BEGIN DESCRIPTION:
Elm 01 90 6136.893
END DESCRIPTION:
XS GIS Cut Line= 4
      1616455.05      6806637.99      1615700.78      6806739.75
      1615317.07      6806817.43      1615141.59      6807048.95
#Sta/Elev= 30
  4238.9 1850.67  4259.1 1848.53  4269.2 1849.11  4275.3 1848.19  4289.4 1847.69
  4410.5 1845.68  4541.7 1844.66  4561.8 1843.67  4894.8 1839.70  4935.2 1840.19
  4955.4 1841.31  4975.6 1835.66  4985.7 1833.72  4993.0 1833.42  4993.3 1832.92
  4997.7 1833.42  5018.8 1833.74  5026.3 1835.38  5036.5 1839.11  5046.7 1839.57
  5148.7 1836.78  5221.6 1837.76  5240.6 1836.98  5317.9 1836.31  5492.6 1835.90
  5650.5 1837.03  5665.0 1836.00  5671.3 1836.04  5678.3 1837.54  5682.0 1837.54
#Mann=3,-1,0
  4238.9    0.05       0  4993.0    0.05       0  4997.7    0.05       0
Bank Sta=4993,4997.7
Exp/Cntr=0.3,0.1

Type RM Length L Ch R = 1,5751,573,573,573
BEGIN DESCRIPTION:
Elm 01 90 5751.29
END DESCRIPTION:
XS GIS Cut Line= 4
      1615840.69      6806202.79      1615607.43      6806385.06
      1615295.58      6806712.60      1615130.74      6807051.12
#Sta/Elev= 30
  4705.3 1839.44  4790.9 1838.48  4840.7 1838.91  4848.8 1837.92  4869.6 1836.88
  4913.0 1836.93  4927.5 1836.24  4933.8 1836.85  4941.0 1836.40  4983.6 1835.86
  5026.4 1835.71  5033.3 1836.37  5040.5 1835.99  5083.0 1835.78  5153.7 1836.72
  5174.8 1836.10  5196.2 1836.78  5203.1 1837.63  5217.3 1836.53  5259.7 1835.55
  5387.1 1835.76  5434.1 1835.25  5434.5 1834.75  5438.5 1834.75  5438.8 1835.25
  5584.0 1835.94  5764.4 1836.02  5803.9 1837.00  5815.5 1836.70  5830.1 1837.58
#Mann=3,-1,0
  4705.3    0.05       0  5434.1    0.05       0  5438.8    0.05       0
Bank Sta=5434.1,5438.8
Exp/Cntr=0.3,0.1

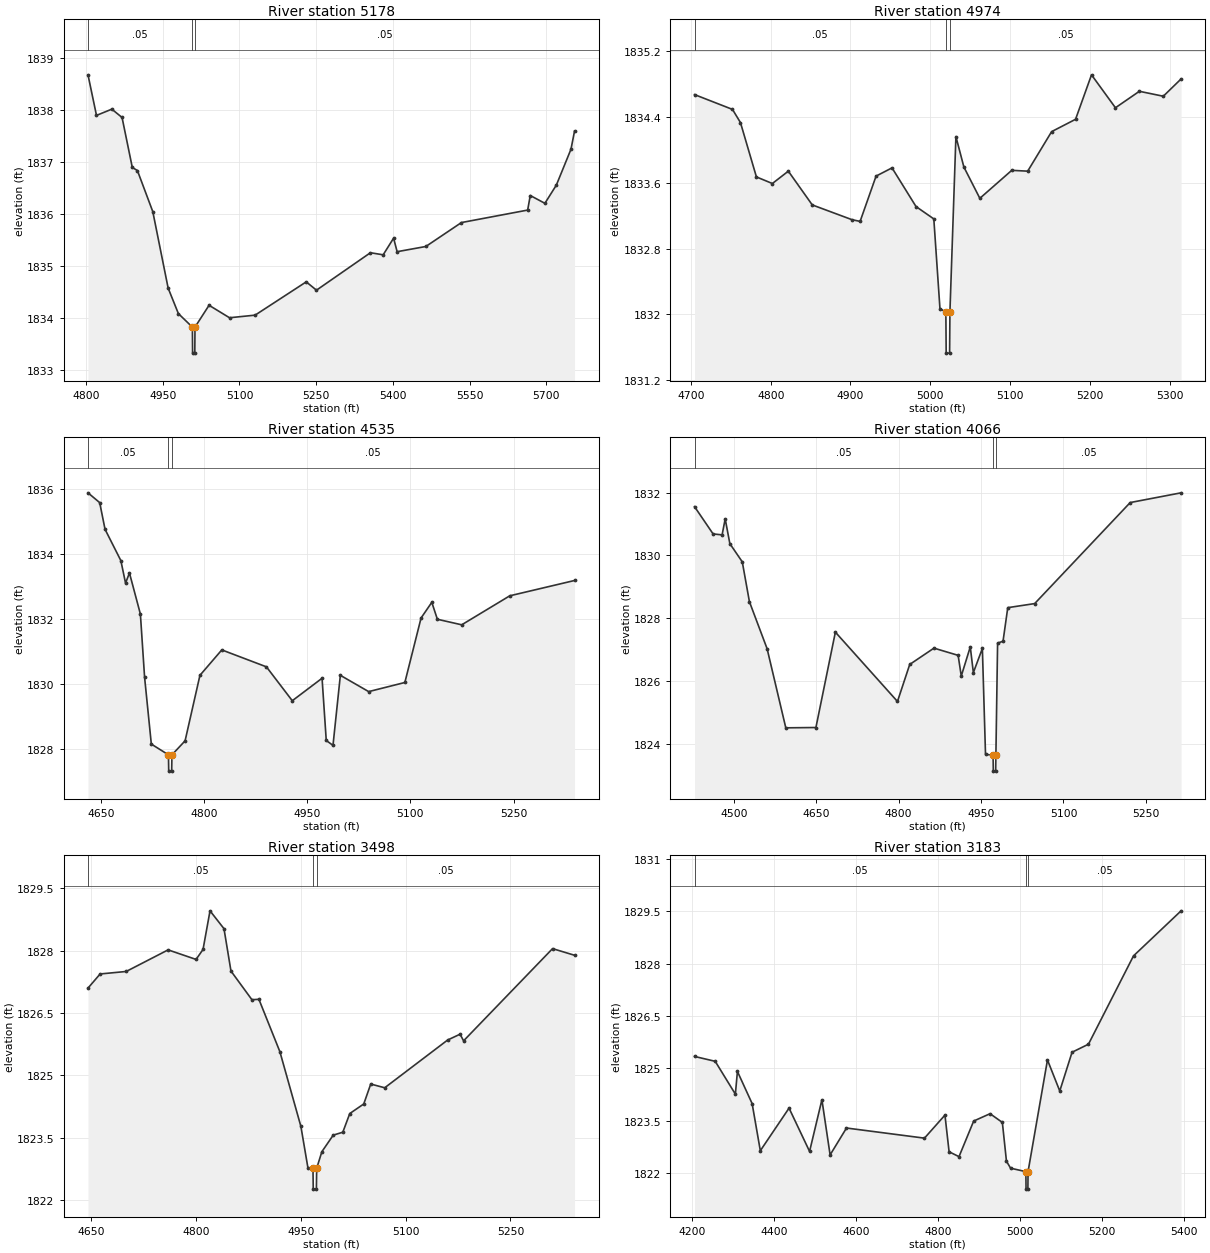
Type RM Length L Ch R = 1,5178,204,204,204
BEGIN DESCRIPTION:
Elm 01 90 5177.79
END DESCRIPTION:
XS GIS Cut Line= 4
      1615194.58      6806101.36      1615197.84      6806298.88
      1615200.48      6806653.99      1615122.43      6807044.91
#Sta/Elev= 30
  4803.9 1838.67  4820.5 1837.89  4850.5 1838.01  4870.5 1837.85  4890.5 1836.89
  4900.5 1836.83  4930.6 1836.04  4960.6 1834.57  4980.6 1834.08  5008.0 1833.82
  5008.4 1833.32  5012.7 1833.32  5013.1 1833.82  5040.6 1834.24  5080.6 1834.00
  5130.6 1834.05  5230.6 1834.69  5250.6 1834.53  5356.1 1835.25  5381.0 1835.21
  5401.4 1835.53  5408.3 1835.27  5464.4 1835.37  5534.0 1835.83  5663.5 1836.07
  5668.6 1836.35  5697.2 1836.20  5719.6 1836.55  5748.2 1837.24  5755.2 1837.59
#Mann=3,-1,0
  4803.9    0.05       0  5008.0    0.05       0  5013.1    0.05       0
Bank Sta=5008,5013.1
Exp/Cntr=0.3,0.1

Type RM Length L Ch R = 1,4974,439,439,439
BEGIN DESCRIPTION:
Elm 01 90 4973.8
END DESCRIPTION:
XS GIS Cut Line= 3
      1615055.70      6806140.42      1615049.18      6806437.77
      1615044.84      6806750.31
#Sta/Elev= 30
  4704.5 1834.67  4752.1 1834.49  4762.1 1834.33  4782.1 1833.67  4802.1 1833.59
  4822.1 1833.74  4852.1 1833.33  4902.1 1833.15  4912.1 1833.13  4932.1 1833.68
  4952.1 1833.78  4982.2 1833.31  5004.5 1833.16  5012.2 1832.07  5019.6 1832.03
  5020.0 1831.53  5024.3 1831.53  5024.7 1832.03  5032.2 1834.16  5042.2 1833.79
  5062.2 1833.41  5102.2 1833.75  5122.2 1833.74  5152.2 1834.22  5182.2 1834.37
  5202.2 1834.91  5232.2 1834.51  5262.2 1834.71  5292.2 1834.65  5314.5 1834.86
#Mann=3,-1,0
  4704.5    0.05       0  5019.6    0.05       0  5024.7    0.05       0
Bank Sta=5019.6,5024.7
Exp/Cntr=0.3,0.1

Type RM Length L Ch R = 1,4535,469,469,469
BEGIN DESCRIPTION:
Elm 01 90 4535.39
END DESCRIPTION:
XS GIS Cut Line= 3
      1614502.60      6806016.40      1614684.89      6806338.67
      1614817.26      6806648.97
#Sta/Elev= 30
  4631.1 1835.87  4648.1 1835.57  4655.9 1834.75  4678.9 1833.79  4685.7 1833.10
  4691.4 1833.41  4707.3 1832.15  4713.4 1830.21  4723.2 1828.16  4748.1 1827.83
  4748.5 1827.33  4752.8 1827.33  4753.2 1827.83  4772.3 1828.26  4793.9 1830.27
  4825.7 1831.05  4890.6 1830.53  4928.2 1829.49  4971.5 1830.18  4977.6 1828.27
  4987.4 1828.12  4998.1 1830.27  5039.3 1829.77  5091.9 1830.05  5115.5 1832.03
  5131.1 1832.51  5139.2 1831.99  5174.6 1831.82  5244.5 1832.71  5338.7 1833.18
#Mann=3,-1,0
  4631.1    0.05       0  4748.1    0.05       0  4753.2    0.05       0
Bank Sta=4748.1,4753.2
Exp/Cntr=0.3,0.1

Type RM Length L Ch R = 1,4066,568,568,568
BEGIN DESCRIPTION:
Elm 01 90 4066.03
END DESCRIPTION:
XS GIS Cut Line= 3
      1613848.11      6806268.31      1614353.76      6806534.16
      1614625.01      6806692.57
#Sta/Elev= 30
  4428.6 1831.55  4462.4 1830.68  4478.8 1830.65  4484.4 1831.16  4492.9 1830.37
  4515.5 1829.79  4528.5 1828.52  4560.7 1827.02  4594.7 1824.50  4649.5 1824.51
  4684.9 1827.55  4797.9 1825.34  4820.2 1826.52  4864.3 1827.04  4908.3 1826.81
  4914.0 1826.15  4930.4 1827.08  4936.0 1826.26  4952.4 1827.03  4958.1 1823.66
  4971.9 1823.62  4972.3 1823.12  4976.6 1823.12  4977.0 1823.62  4980.1 1827.20
  4990.0 1827.26  4998.6 1828.33  5047.6 1828.46  5221.4 1831.68  5314.0 1831.99
#Mann=3,-1,0
  4428.6    0.05       0  4971.9    0.05       0  4977.0    0.05       0
Bank Sta=4971.9,4977
Exp/Cntr=0.3,0.1

Type RM Length L Ch R = 1,3498,315,315,315
BEGIN DESCRIPTION:
Elm 01 90 3498.29
END DESCRIPTION:
XS GIS Cut Line= 3
      1613600.34      6806723.37      1613952.72      6806714.69
      1614296.48      6806730.32
#Sta/Elev= 30
  4645.2 1827.10  4662.6 1827.44  4699.9 1827.50  4759.9 1828.02  4799.9 1827.79
  4809.9 1828.03  4819.9 1828.96  4839.9 1828.53  4849.9 1827.51  4879.9 1826.82
  4889.9 1826.83  4919.9 1825.57  4950.0 1823.77  4960.0 1822.78  4967.3 1822.76
  4967.7 1822.26  4972.2 1822.26  4972.6 1822.76  4980.0 1823.16  4996.3 1823.56
  5010.0 1823.63  5020.0 1824.08  5040.0 1824.31  5050.0 1824.79  5070.0 1824.70
  5160.1 1825.85  5177.9 1825.99  5182.9 1825.83  5310.3 1828.05  5341.8 1827.89
#Mann=3,-1,0
  4645.2    0.05       0  4967.3    0.05       0  4972.6    0.05       0
Bank Sta=4967.3,4972.6
Exp/Cntr=0.3,0.1

Type RM Length L Ch R = 1,3183,155,155,155
BEGIN DESCRIPTION:
Elm 01 90 3183.25
END DESCRIPTION:
XS GIS Cut Line= 4
      1613164.59      6807018.57      1613709.34      6806989.28
      1613958.05      6806998.61      1614351.07      6806991.68
#Sta/Elev= 30
  4206.5 1825.34  4257.0 1825.20  4306.2 1824.26  4311.2 1824.91  4347.1 1823.99
  4367.1 1822.64  4437.2 1823.86  4487.3 1822.62  4517.4 1824.10  4537.4 1822.52
  4577.4 1823.29  4767.7 1823.00  4817.7 1823.66  4827.8 1822.61  4852.0 1822.47
  4887.8 1823.49  4927.8 1823.70  4957.8 1823.45  4967.8 1822.34  4977.9 1822.14
  5015.2 1822.04  5015.6 1821.54  5020.1 1821.54  5020.5 1822.04  5067.9 1825.24
  5097.9 1824.35  5127.9 1825.46  5167.9 1825.69  5277.9 1828.22  5394.0 1829.51
#Mann=3,-1,0
  4206.5    0.05       0  5015.2    0.05       0  5020.5    0.05       0
Bank Sta=5015.2,5020.5
Exp/Cntr=0.3,0.1

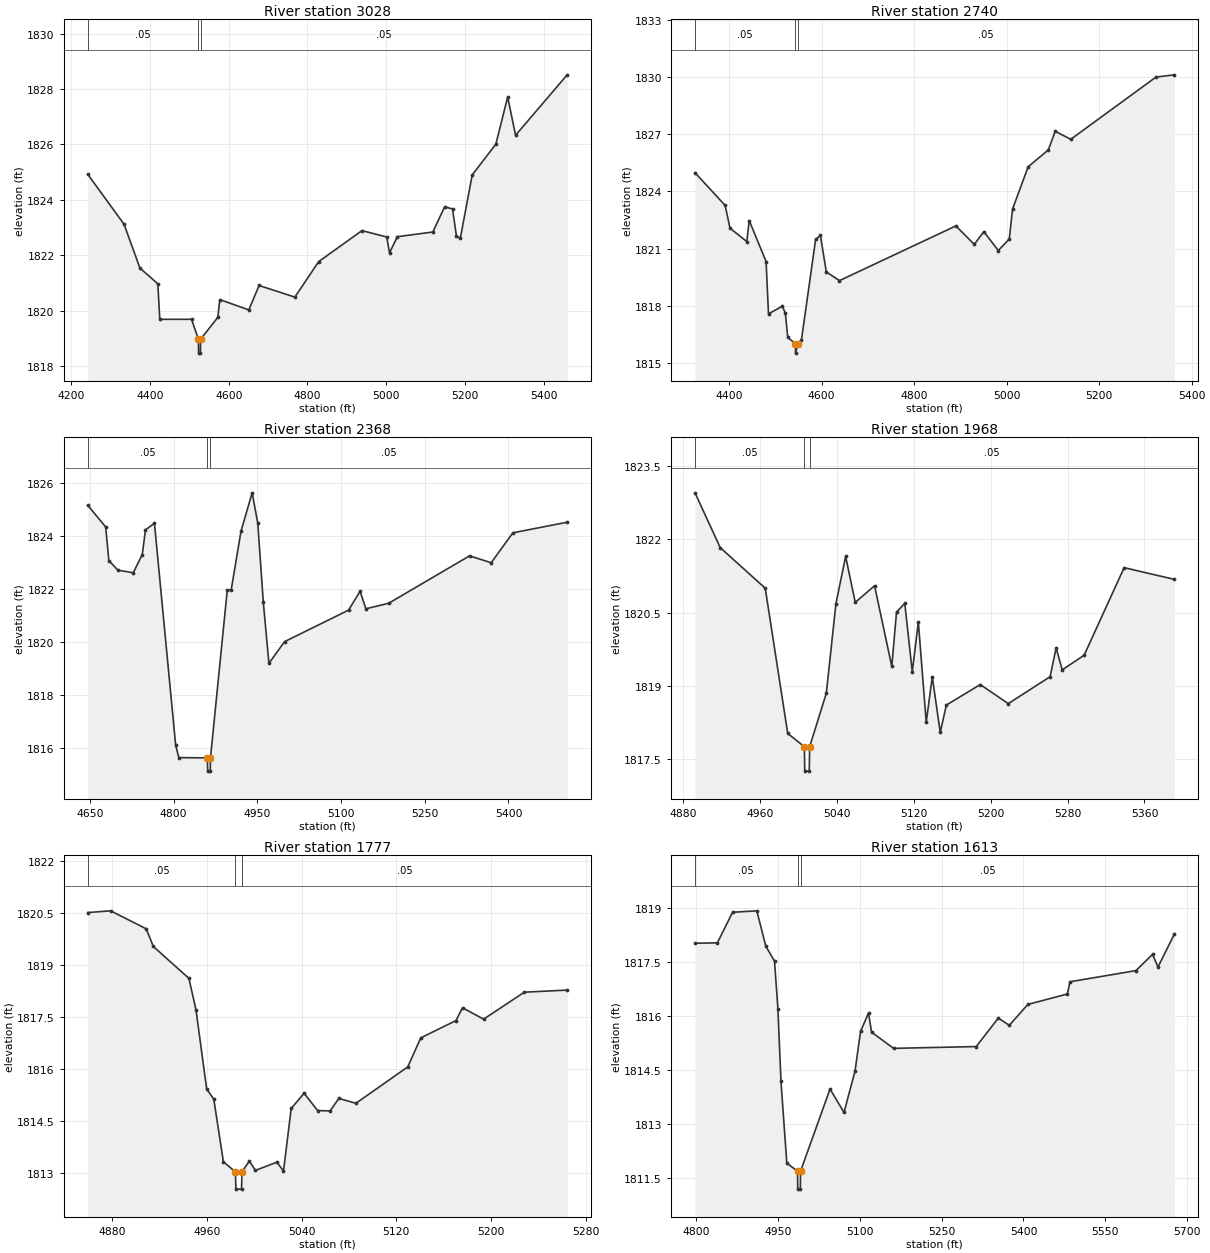
Type RM Length L Ch R = 1,3028,288,288,288
BEGIN DESCRIPTION:
Elm 01 90 3028
END DESCRIPTION:
XS GIS Cut Line= 4
      1613153.72      6807059.80      1613720.16      6807134.27
      1613905.96      6807135.76      1614366.02      6807146.17
#Sta/Elev= 30
  4242.1 1824.92  4334.2 1823.12  4374.5 1821.54  4420.0 1820.97  4425.0 1819.69
  4505.6 1819.69  4523.1 1818.97  4523.5 1818.47  4528.1 1818.47  4528.6 1818.97
  4572.3 1819.76  4577.4 1820.40  4651.1 1820.03  4677.1 1820.91  4767.9 1820.49
  4828.3 1821.77  4938.3 1822.89  5001.2 1822.66  5008.3 1822.09  5028.3 1822.67
  5118.3 1822.84  5148.3 1823.75  5168.3 1823.67  5178.3 1822.68  5188.3 1822.63
  5218.3 1824.90  5278.3 1826.01  5308.3 1827.71  5328.3 1826.33  5459.4 1828.51
#Mann=3,-1,0
  4242.1    0.05       0  4523.1    0.03       0  4528.6    0.05       0
Bank Sta=4523.1,4528.6
Exp/Cntr=0.3,0.1

Type RM Length L Ch R = 1,2740,372,372,372
BEGIN DESCRIPTION:
Elm 01 90 2739.96
END DESCRIPTION:
XS GIS Cut Line= 4
      1613151.59      6807066.32      1613660.01      6807190.44
      1613701.10      6807338.88      1613779.23      6807689.61
#Sta/Elev= 30
  4326.1 1824.98  4391.3 1823.26  4401.7 1822.07  4438.1 1821.37  4443.3 1822.47
  4479.8 1820.32  4485.0 1817.58  4514.9 1817.98  4521.5 1817.62  4526.6 1816.34
  4543.0 1816.02  4543.5 1815.52  4548.5 1816.02  4556.1 1816.19  4586.9 1821.48
  4597.2 1821.69  4610.0 1819.78  4638.4 1819.32  4890.2 1822.19  4929.9 1821.22
  4950.7 1821.89  4981.8 1820.90  5005.6 1821.50  5012.8 1823.08  5046.5 1825.29
  5090.0 1826.17  5105.0 1827.15  5138.6 1826.73  5322.8 1829.99  5362.8 1830.11
#Mann=3,-1,0
  4326.1    0.05       0  4543.0    0.05       0  4548.5    0.05       0
Bank Sta=4543,4548.5
Exp/Cntr=0.3,0.1

Type RM Length L Ch R = 1,2368,400,400,400
BEGIN DESCRIPTION:
Elm 01 90 2368.97
END DESCRIPTION:
XS GIS Cut Line= 5
      1613134.22      6807066.32      1613357.73      6807187.84
      1613359.74      6807289.14      1613332.30      6807410.32
      1613437.62      6807774.52
#Sta/Elev= 30
  4646.1 1825.16  4678.2 1824.34  4683.9 1823.07  4700.1 1822.71  4727.6 1822.61
  4743.8 1823.30  4749.5 1824.23  4765.6 1824.48  4803.6 1816.10  4809.3 1815.63
  4860.5 1815.62  4861.0 1815.12  4865.6 1815.12  4866.0 1815.62  4896.1 1821.96
  4903.1 1821.96  4920.7 1824.18  4940.7 1825.63  4950.7 1824.49  4960.7 1821.49
  4970.7 1819.19  4998.8 1820.01  5113.4 1821.20  5134.1 1821.91  5144.5 1821.25
  5185.4 1821.46  5330.2 1823.25  5369.0 1822.99  5407.9 1824.12  5505.2 1824.52
#Mann=3,-1,0
  4646.1    0.05       0  4860.5    0.05       0  4866.0    0.05       0
Bank Sta=4860.5,4866
Exp/Cntr=0.3,0.1

Type RM Length L Ch R = 1,1968,191,191,191
BEGIN DESCRIPTION:
Elm 01 90 1968.08
END DESCRIPTION:
XS GIS Cut Line= 4
      1613014.69      6807231.84      1613022.50      6807341.23
      1613030.31      6807442.79      1613204.78      6807670.64
#Sta/Elev= 30
  4892.7 1822.95  4918.9 1821.83  4965.7 1821.00  4989.1 1818.03  5006.4 1817.76
  5006.8 1817.26  5011.5 1817.26  5011.9 1817.76  5029.2 1818.85  5039.2 1820.68
  5049.3 1821.65  5059.3 1820.71  5079.4 1821.05  5097.3 1819.40  5102.2 1820.51
  5110.8 1820.69  5118.6 1819.29  5124.9 1820.31  5133.1 1818.26  5139.4 1819.19
  5147.7 1818.05  5154.0 1818.61  5189.3 1819.03  5218.4 1818.64  5261.9 1819.19
  5268.2 1819.78  5274.5 1819.33  5297.3 1819.63  5338.9 1821.42  5391.2 1821.18
#Mann=3,-1,0
  4892.7    0.05       0  5006.4    0.05       0  5011.9    0.05       0
Bank Sta=5006.4,5011.9
Exp/Cntr=0.3,0.1

Type RM Length L Ch R = 1,1777,164,164,164
BEGIN DESCRIPTION:
Elm 01 90 1776.97
END DESCRIPTION:
XS GIS Cut Line= 3
      1612781.94      6807313.01      1612861.37      6807431.51
      1612966.82      6807671.06
#Sta/Elev= 30
  4859.7 1820.52  4879.0 1820.57  4909.0 1820.05  4915.0 1819.54  4945.0 1818.62
  4951.0 1817.71  4960.0 1815.42  4966.0 1815.13  4974.1 1813.32  4984.2 1813.03
  4984.7 1812.53  4989.4 1812.53  4989.8 1813.03  4996.0 1813.34  5001.1 1813.07
  5019.3 1813.31  5024.8 1813.05  5031.3 1814.86  5042.2 1815.30  5053.6 1814.80
  5064.1 1814.79  5071.5 1815.15  5085.9 1815.01  5129.6 1816.06  5140.6 1816.90
  5170.3 1817.40  5175.8 1817.77  5193.6 1817.44  5228.0 1818.22  5264.1 1818.28
#Mann=3,-1,0
  4859.7    0.05       0  4984.2    0.05       0  4989.8    0.05       0
Bank Sta=4984.2,4989.8
Exp/Cntr=0.3,0.1

Type RM Length L Ch R = 1,1613,204,204,204
BEGIN DESCRIPTION:
Elm 01 90 1612.75
END DESCRIPTION:
XS GIS Cut Line= 4
      1612620.25      6807308.44      1612714.01      6807490.75
      1612742.20      6807686.86      1612806.51      6808157.85
#Sta/Elev= 30
  4798.1 1818.02  4839.1 1818.03  4866.9 1818.88  4911.3 1818.92  4927.8 1817.94
  4943.8 1817.52  4950.0 1816.19  4955.6 1814.18  4966.3 1811.91  4985.9 1811.69
  4986.4 1811.19  4991.1 1811.19  4991.5 1811.69  5045.5 1813.97  5071.1 1813.32
  5091.3 1814.47  5101.4 1815.57  5116.0 1816.08  5121.6 1815.55  5162.0 1815.10
  5313.4 1815.15  5353.8 1815.94  5374.0 1815.74  5408.0 1816.32  5480.3 1816.61
  5485.3 1816.95  5606.1 1817.26  5636.4 1817.71  5646.5 1817.36  5676.6 1818.28
#Mann=3,-1,0
  4798.1    0.05       0  4985.9    0.05       0  4991.5    0.05       0
Bank Sta=4985.9,4991.5
Exp/Cntr=0.3,0.1

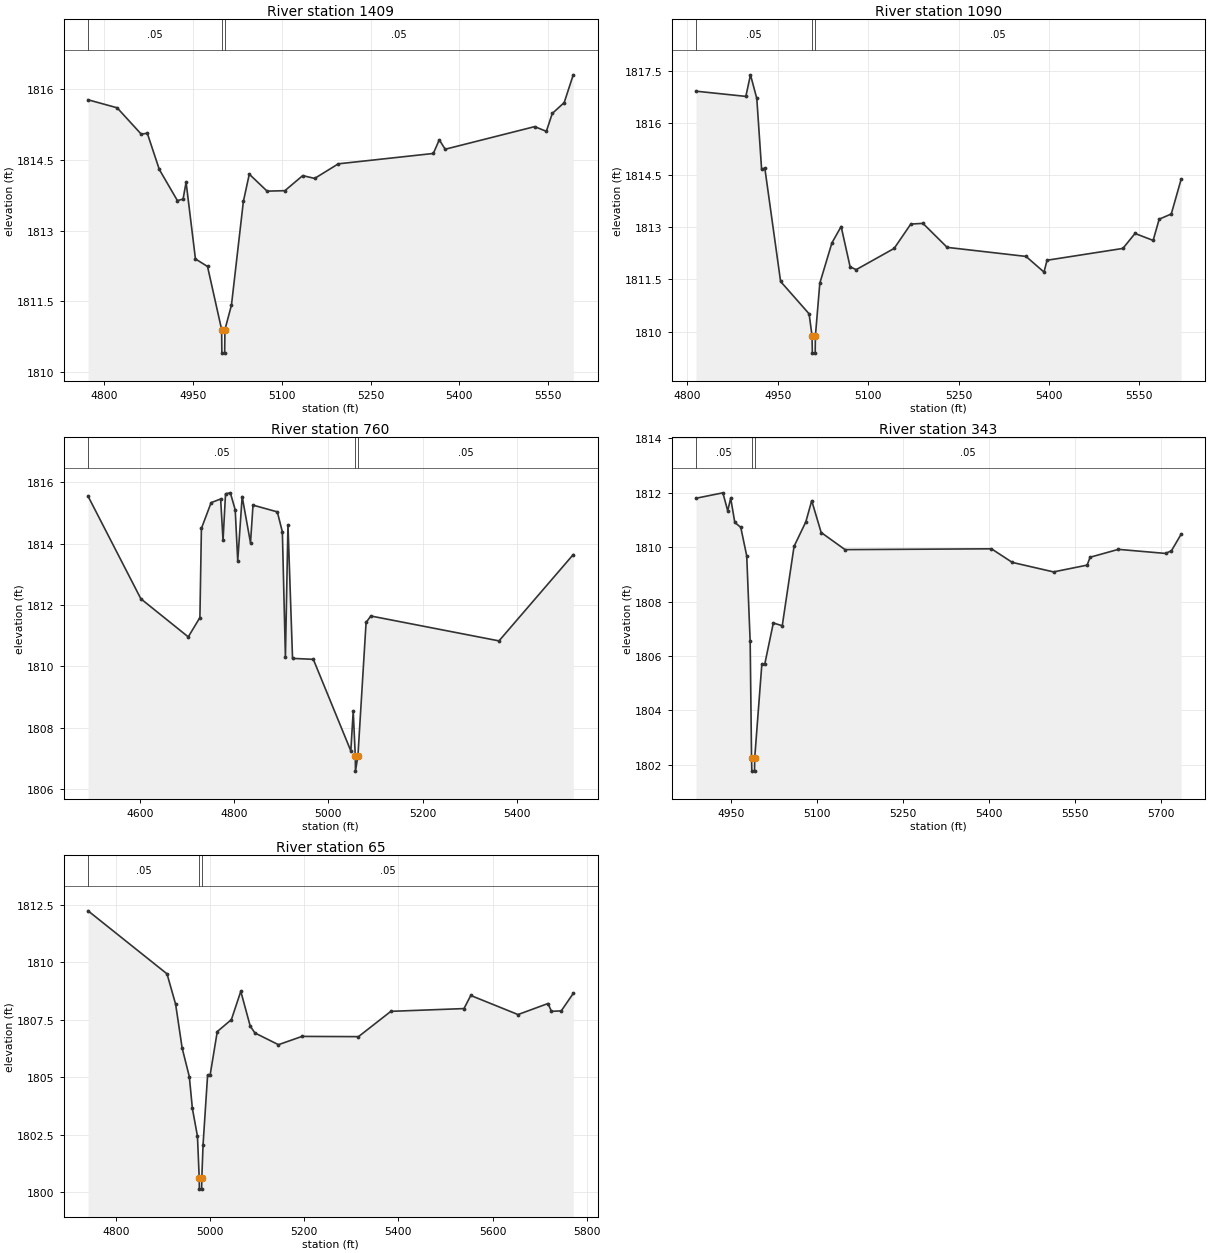
Type RM Length L Ch R = 1,1409,319,319,319
BEGIN DESCRIPTION:
Elm 01 90 1408.51
END DESCRIPTION:
XS GIS Cut Line= 4
      1612490.05      6807339.70      1612531.72      6807565.40
      1612556.90      6807943.05      1612576.45      6808153.24
#Sta/Elev= 30
  4773.1 1815.78  4822.2 1815.61  4862.9 1815.05  4873.1 1815.07  4893.4 1814.30
  4923.9 1813.64  4933.5 1813.67  4938.6 1814.03  4954.4 1812.40  4974.8 1812.24
  4998.6 1810.90  4999.0 1810.40  5003.7 1810.40  5004.2 1810.90  5015.2 1811.42
  5035.3 1813.62  5045.3 1814.20  5075.4 1813.84  5105.4 1813.85  5135.5 1814.17
  5155.6 1814.11  5195.6 1814.42  5356.0 1814.64  5366.0 1814.93  5376.0 1814.73
  5527.1 1815.21  5546.8 1815.11  5556.8 1815.49  5576.9 1815.72  5592.2 1816.31
#Mann=3,-1,0
  4773.1    0.05       0  4998.6    0.05       0  5004.2    0.05       0
Bank Sta=4998.6,5004.2
Exp/Cntr=0.3,0.1

Type RM Length L Ch R = 1,1090,330,330,330
BEGIN DESCRIPTION:
Elm 01 90 1090.47
END DESCRIPTION:
XS GIS Cut Line= 4
      1612295.62      6807362.24      1612236.58      6807537.62
      1612183.91      6807983.80      1612196.61      6808154.40
#Sta/Elev= 30
  4814.1 1816.91  4896.9 1816.76  4904.6 1817.38  4915.1 1816.70  4923.1 1814.66
  4928.4 1814.70  4954.6 1811.44  5001.9 1810.51  5006.8 1809.88  5007.3 1809.38
  5012.0 1809.38  5012.4 1809.88  5019.7 1811.39  5039.8 1812.55  5055.1 1813.02
  5070.0 1811.86  5080.1 1811.78  5143.1 1812.39  5170.7 1813.09  5190.9 1813.11
  5231.1 1812.42  5362.0 1812.16  5391.8 1811.71  5396.9 1812.05  5522.8 1812.39
  5542.9 1812.82  5573.0 1812.62  5583.0 1813.23  5603.1 1813.38  5619.5 1814.38
#Mann=3,-1,0
  4814.1    0.05       0  5006.8    0.05       0  5012.4    0.05       0
Bank Sta=5006.8,5012.4
Exp/Cntr=0.3,0.1

Type RM Length L Ch R = 1,760,417,417,417
BEGIN DESCRIPTION:
Elm 01 90 760.45
END DESCRIPTION:
XS GIS Cut Line= 6
      1612229.64      6807357.07      1612003.94      6807443.87
      1611929.29      6807459.50      1611911.93      6807509.85
      1611964.01      6807640.06      1612027.28      6808154.40
#Sta/Elev= 30
  4490.0 1815.54  4602.1 1812.20  4702.7 1810.96  4727.4 1811.59  4730.6 1814.49
  4751.2 1815.33  4771.4 1815.45  4776.5 1814.10  4781.8 1815.62  4792.0 1815.65
  4802.3 1815.10  4807.7 1813.44  4817.1 1815.53  4834.8 1814.02  4840.1 1815.25
  4891.7 1815.03  4902.4 1814.38  4908.9 1810.30  4914.3 1814.61  4924.0 1810.26
  4968.1 1810.23  5047.7 1807.25  5052.8 1808.54  5057.2 1807.09  5057.6 1806.59
  5062.8 1807.09  5080.1 1811.43  5090.2 1811.64  5362.2 1810.83  5519.8 1813.64
#Mann=3,-1,0
  4490.0    0.05       0  5057.2    0.05       0  5062.8    0.05       0
Bank Sta=5057.2,5062.8
Exp/Cntr=0.3,0.1

Type RM Length L Ch R = 1,343,278,278,278
BEGIN DESCRIPTION:
Elm 01 90 343.38
END DESCRIPTION:
XS GIS Cut Line= 3
      1611634.14      6807332.73      1611665.40      6807443.87
      1611838.31      6808154.39
#Sta/Elev= 30
  4888.6 1811.80  4935.6 1812.00  4944.0 1811.34  4949.2 1811.80  4956.4 1810.91
  4966.8 1810.73  4977.2 1809.68  4983.2 1806.53  4985.6 1802.26  4986.1 1801.76
  4990.8 1801.76  4991.2 1802.26  5003.6 1805.70  5008.7 1805.70  5023.6 1807.21
  5039.2 1807.11  5059.8 1810.03  5080.3 1810.93  5090.6 1811.71  5107.1 1810.54
  5148.8 1809.91  5404.3 1809.94  5440.6 1809.44  5512.6 1809.09  5571.2 1809.34
  5576.4 1809.63  5625.8 1809.92  5708.1 1809.77  5718.4 1809.87  5735.3 1810.48
#Mann=3,-1,0
  4888.6    0.05       0  4985.6    0.05       0  4991.2    0.05       0
Bank Sta=4985.6,4991.2
Exp/Cntr=0.3,0.1

Type RM Length L Ch R = 1,65,0,0,0
BEGIN DESCRIPTION:
Elm 01 90 3390.298
END DESCRIPTION:
XS GIS Cut Line= 5
      1611575.59      6807326.68      1611454.52      6807359.28
      1611402.41      6807482.86      1611406.78      6807817.18
      1611678.07      6808160.10
#Sta/Elev= 30
  4740.5 1812.24  4908.3 1809.50  4926.6 1808.18  4940.5 1806.27  4955.7 1805.03
  4962.2 1803.65  4973.0 1802.44  4976.7 1800.64  4977.1 1800.14  4981.8 1800.14
  4982.3 1800.64  4984.9 1802.07  4994.6 1805.11  5000.0 1805.11  5015.1 1806.99
  5045.1 1807.51  5065.1 1808.74  5085.1 1807.23  5095.1 1806.93  5145.1 1806.42
  5195.2 1806.78  5315.2 1806.77  5384.0 1807.87  5539.4 1807.99  5553.8 1808.56
  5654.2 1807.73  5717.9 1808.21  5725.3 1807.87  5746.1 1807.89  5771.6 1808.65
#Mann=3,-1,0
  4740.5    0.05       0  4976.7    0.05       0  4982.3    0.05       0
Bank Sta=4976.7,4982.3
Exp/Cntr=0.3,0.1

Chan Stop Cuts=-1