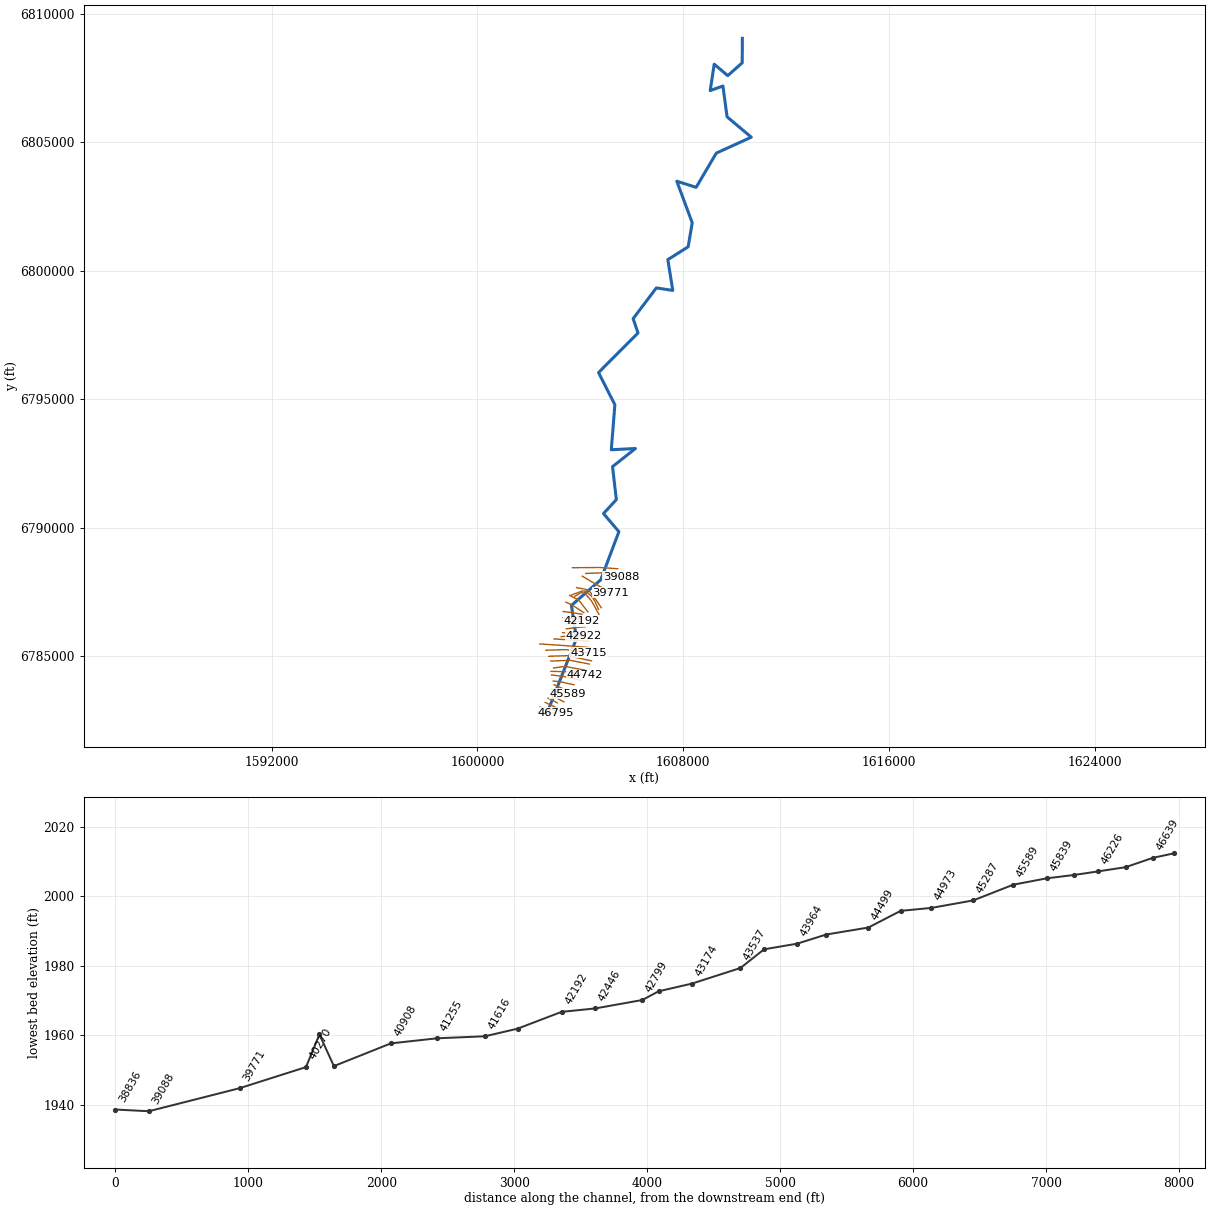
--- Elm 01 91.prj (project) ---

Proj Title=Elm 01 91 Base Level Engineering
Current Plan=p01
Default Exp/Contr=0.3,0.1
English Units
Geom File=g01
Flow File=f01
Plan File=p01
Y Axis Title=Elevation
X Axis Title(PF)=Main Channel Distance
X Axis Title(XS)=Station
BEGIN DESCRIPTION:
Elm 01 91
END DESCRIPTION:
DSS Export Rating Curves= 0
DSS Export Rating Curve Sorted= 0
DSS Export Volume Flow Curves= 0
DXF OffsetX= 0
DXF OffsetY= 0
DXF ScaleX= 1
DXF ScaleY= 10

--- Elm 01 91.p01 (plan) ---

Plan Title=Multiple Run
Short Identifier=Multiple
Geom File=g01
Flow File=f01
Subcritical Flow
K Sum by GR= 0
Std Step Tol= 0.01
Critical Tol= 0.01
Num of Std Step Trials= 20
Max Error Tol= 0.3
Flow Tol Ratio= 0.001
Split Flow NTrial= 30
Split Flow Tol= 0.02
Split Flow Ratio= 0.02
Log Output Level= 0
Friction Slope Method= 1
Unsteady Friction Slope Method= 2
Unsteady Bridges Friction Slope Method= 1
Parabolic Critical Depth
Global Vel Dist=  1 , 1 , 1
Global Log Level= 0
CheckData=True
Encroach Param= -1, 0, 0, 0
BEGIN DESCRIPTION:
Multiple Run
END DESCRIPTION:

--- Elm 01 91.f01 (steady flow) ---

Flow Title=Multiple
Program Version=4.10
Number of Profiles= 7
Profile Names=10-year,25-year,50-year,1pct_min,100-year,1pct_plu,500-year
River Rch & RM=Elm 01 91,Reach-1         ,46795
     412     602     768     609     977    1340    1600
River Rch & RM=Elm 01 91,Reach-1         ,46047
     486     709     904     715    1150    1580    1870
River Rch & RM=Elm 01 91,Reach-1         ,40371
     543     799    1020     812    1300    1790    2140
River Rch & RM=Elm 01 91,Reach-1         ,38836
     661     977    1260     999    1600    2200    2640
River Rch & RM=Elm 01 91,Reach-1         ,38069
     661     977    1260     999    1600    2200    2640
River Rch & RM=Elm 01 91,Reach-1         ,31953
     735    1090    1400    1110    1780    2450    2940
River Rch & RM=Elm 01 91,Reach-1         ,28489
     776    1150    1480    1170    1880    2590    3090
River Rch & RM=Elm 01 91,Reach-1         ,27231
     776    1150    1480    1170    1880    2590    3090
River Rch & RM=Elm 01 91,Reach-1         ,22961
    1070    1590    2050    1630    2620    3600    4320
River Rch & RM=Elm 01 91,Reach-1         ,13534
    1060    1570    2020    1600    2570    3530    4220
River Rch & RM=Elm 01 91,Reach-1         ,11574
    1160    1720    2210    1750    2810    3870    4610
River Rch & RM=Elm 01 91,Reach-1         ,22
    2080    3140    4080    3270    5240    7210    8770
Boundary for River Rch & Prof#=Elm 01 91,Reach-1         , 1
Up Type= 0
Dn Type= 3
Dn Slope=0.001
Boundary for River Rch & Prof#=Elm 01 91,Reach-1         , 2
Up Type= 0
Dn Type= 3
Dn Slope=0.001
Boundary for River Rch & Prof#=Elm 01 91,Reach-1         , 3
Up Type= 0
Dn Type= 3
Dn Slope=0.001
Boundary for River Rch & Prof#=Elm 01 91,Reach-1         , 4
Up Type= 0
Dn Type= 3
Dn Slope=0.001
Boundary for River Rch & Prof#=Elm 01 91,Reach-1         , 5
Up Type= 0
Dn Type= 3
Dn Slope=0.001
Boundary for River Rch & Prof#=Elm 01 91,Reach-1         , 6
Up Type= 0
Dn Type= 3
Dn Slope=0.001
Boundary for River Rch & Prof#=Elm 01 91,Reach-1         , 7
Up Type= 0
Dn Type= 3
Dn Slope=0.001
DSS Import GetInterval= 0
DSS Import GetPeak= 0
DSS Import FillOption= 0

--- Elm 01 91.g01 (geometry) ---

Geom Title=Existing Conditions
Program Version=4.10

River Reach=Elm 01 91       ,Reach-1
Reach XY= 30
        1602705.        6782788.      1603853.08      6785693.98
        1603658.       6786986.6      1604799.64       6787985.3
      1605504.51      6789853.22      1604904.51      6790558.12
      1605404.14      6791098.31      1605256.95      6792382.11
      1606148.03      6793088.25      1605208.53      6793039.45
      1605347.69      6794788.04      1604712.58      6796041.35
      1606247.33      6797581.48      1606058.03      6798136.61
      1606960.44      6799332.75      1607599.55      6799235.53
      1607407.16      6800432.57      1608197.54      6800931.95
      1608355.53      6801862.86      1607756.67      6803482.33
      1608507.46      6803243.45      1609291.43      6804574.53
      1610652.92      6805193.49       1609710.4      6805985.57
      1609549.78      6807183.45      1609054.73      6807006.45
      1609210.25      6808032.56      1609736.59      6807587.63
      1610299.54      6808085.55        1610305.        6809038.

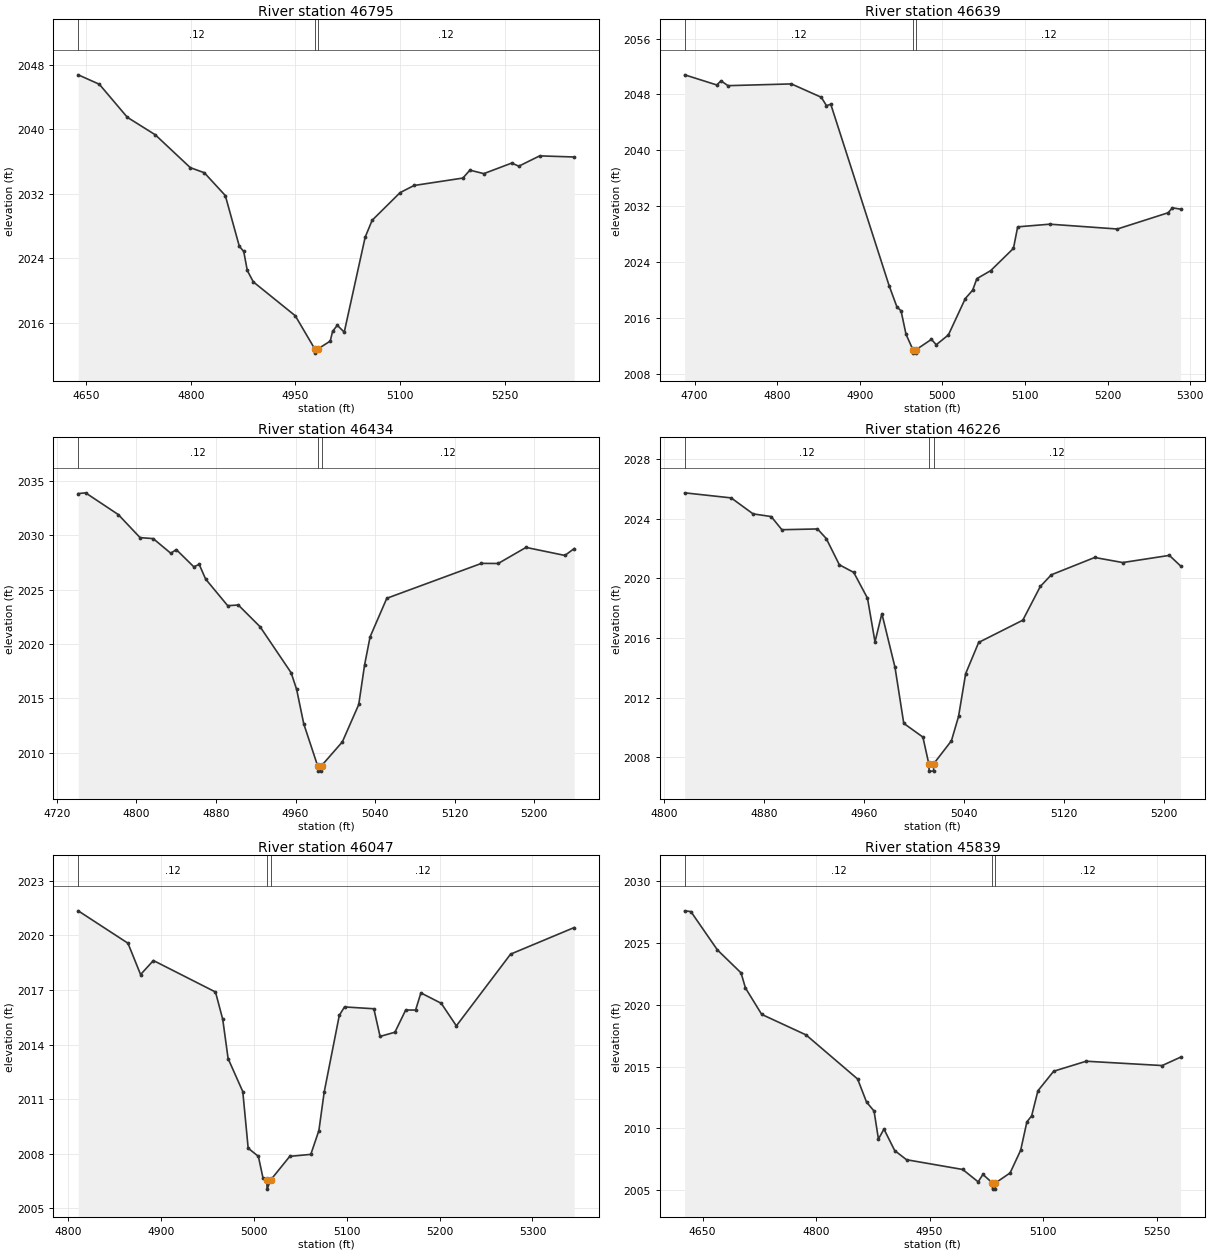
Type RM Length L Ch R = 1 ,46795   ,156,156,156
BEGIN DESCRIPTION:
Elm 01 91 46699.719
END DESCRIPTION:
XS GIS Cut Line= 3
      1602344.78      6782842.36      1602704.89      6782813.06
      1603054.39      6782801.12
#Sta/Elev= 30
  4638.7 2046.74    4669 2045.57  4709.1 2041.48  4749.2 2039.31  4799.4 2035.24
  4819.5 2034.61  4849.6 2031.78  4869.7 2025.49    4876 2024.86  4881.1  2022.5
  4889.7 2021.09  4949.9 2016.89    4978 2012.76  4978.3 2012.26    4982 2012.76
    5000 2013.75  5003.4 2014.96  5010.1 2015.71  5020.1 2014.86  5050.1 2026.63
  5060.1 2028.72  5100.2 2032.15  5120.2 2033.03  5190.2 2033.95  5200.2 2034.93
  5220.2  2034.5  5260.3 2035.81  5270.3 2035.42  5300.3  2036.7  5349.7 2036.56
#Mann= 3 ,-1 , 0
  4638.7     .12       0    4978     .07       0    4982     .12       0
Bank Sta=4978,4982
XS Rating Curve= 0 ,0
Exp/Cntr=0.3,0.1

Type RM Length L Ch R = 1 ,46639   ,205,205,205
BEGIN DESCRIPTION:
Elm 01 91 46639.47
END DESCRIPTION:
XS GIS Cut Line= 3
      1602423.96      6783032.25      1602726.73      6782961.71
       1603009.9      6782900.96
#Sta/Elev= 30
  4687.9 2050.81  4726.8 2049.36  4731.9 2049.95  4740.3 2049.26  4817.1 2049.51
  4853.3  2047.6  4859.6  2046.4  4864.8  2046.6  4935.4 2020.66  4944.8 2017.63
  4949.9 2017.04  4955.9 2013.69  4964.2 2011.49  4964.5 2010.99    4968 2010.99
  4968.2 2011.49  4986.7 2012.96  4992.5 2012.19  5007.2 2013.59  5027.7  2018.8
  5036.6    2020  5041.7 2021.65  5058.4 2022.79    5086 2025.98  5091.1 2029.06
    5130 2029.44  5211.8 2028.75  5273.2 2031.07  5278.5 2031.78  5288.4 2031.59
#Mann= 3 ,-1 , 0
  4687.9     .12       0  4964.2     .07       0  4968.2     .12       0
Bank Sta=4964.2,4968.2
XS Rating Curve= 0 ,0
Exp/Cntr=0.3,0.1

Type RM Length L Ch R = 1 ,46434   ,208,208,208
BEGIN DESCRIPTION:
Elm 01 91 46433.91
END DESCRIPTION:
XS GIS Cut Line= 3
      1602638.29      6783212.72      1602872.69      6783106.81
      1603088.86      6782999.16
#Sta/Elev= 30
  4741.5 2033.83  4748.9  2033.9  4781.8  2031.9  4803.7 2029.78  4816.9 2029.69
  4834.6 2028.34  4840.1 2028.68  4857.7  2027.1  4863.2 2027.31  4869.6 2025.97
  4891.8 2023.52  4902.5 2023.58  4924.4 2021.58  4955.6 2017.35  4961.1 2015.83
  4968.3 2012.65  4982.2  2008.8  4982.5  2008.3    4986  2008.3  4986.2  2008.8
  5007.1 2010.99  5023.6 2014.43  5029.5 2018.09    5035 2020.65  5051.8  2024.2
    5147 2027.41  5163.8  2027.4  5191.8 2028.88  5230.9 2028.14  5240.2 2028.77
#Mann= 3 ,-1 , 0
  4741.5     .12       0  4982.2     .07       0  4986.2     .12       0
Bank Sta=4982.2,4986.2
XS Rating Curve= 0 ,0
Exp/Cntr=0.3,0.1

Type RM Length L Ch R = 1 ,46226   ,179,179,179
BEGIN DESCRIPTION:
Elm 01 91 46225.71
END DESCRIPTION:
XS GIS Cut Line= 3
      1602752.09       6783376.6      1602918.79      6783300.19
      1603105.61      6783197.41
#Sta/Elev= 30
  4816.6 2025.72  4853.8 2025.38  4871.3 2024.31  4885.8 2024.13  4894.3 2023.25
  4922.8  2023.3  4929.8 2022.66  4940.3  2020.9  4951.8 2020.39  4962.8 2018.66
  4968.8 2015.74  4974.3 2017.63  4984.8 2014.03  4991.8 2010.28  5007.1 2009.36
  5011.8 2007.58  5012.1 2007.08  5015.6 2007.08  5015.8 2007.58  5029.9 2009.11
  5035.6 2010.74  5041.3 2013.61  5051.7  2015.7    5087 2017.19    5101 2019.45
  5109.8 2020.23  5144.5 2021.39  5166.9 2021.05  5204.2 2021.53  5213.2 2020.82
#Mann= 3 ,-1 , 0
  4816.6     .12       0  5011.8     .07       0  5015.8     .12       0
Bank Sta=5011.8,5015.8
XS Rating Curve= 0 ,0
Exp/Cntr=0.3,0.1

Type RM Length L Ch R = 1 ,46047   ,208,208,208
BEGIN DESCRIPTION:
Elm 01 91 46047.28
END DESCRIPTION:
XS GIS Cut Line= 3
      1602896.72      6783491.53      1603061.32      6783397.07
      1603365.48      6783235.27
#Sta/Elev= 30
  4810.6 2021.35  4864.2 2019.57  4877.8 2017.85  4891.6 2018.62  4958.5 2016.89
  4966.3 2015.39  4972.1 2013.23  4987.9 2011.42  4993.7 2008.31  5004.7 2007.86
  5009.6 2006.69  5013.8 2006.56  5014.1 2006.06  5017.9 2006.56  5038.5 2007.86
  5061.2 2007.97  5069.9 2009.28  5075.6 2011.39  5091.9 2015.61  5097.5 2016.07
  5129.1 2015.97  5135.8 2014.45  5151.8 2014.68  5163.4  2015.9  5174.1  2015.9
  5179.8 2016.84  5201.7 2016.27    5218 2015.03  5276.4 2018.97  5344.9 2020.43
#Mann= 3 ,-1 , 0
  4810.6     .12       0  5013.8     .07       0  5017.9     .12       0
Bank Sta=5013.8,5017.9
XS Rating Curve= 0 ,0
Exp/Cntr=0.3,0.1

Type RM Length L Ch R = 1 ,45839   ,250,250,250
BEGIN DESCRIPTION:
Elm 01 91 45838.81
END DESCRIPTION:
XS GIS Cut Line= 3
      1602887.93      6783732.01      1603209.98      6783542.77
      1603434.31      6783371.94
#Sta/Elev= 30
  4626.3  2027.6  4634.5 2027.54  4669.5 2024.44  4700.8 2022.58  4706.6 2021.36
  4728.1 2019.22  4786.7 2017.56  4854.9 2013.99  4866.7 2012.12  4876.6  2011.4
  4882.4 2009.13  4889.7 2009.94  4903.9  2008.2  4919.5 2007.46  4993.8 2006.67
  5014.2 2005.67  5020.5 2006.27    5033 2005.58  5033.2 2005.08  5036.8 2005.08
  5037.1 2005.58  5056.4 2006.39  5070.4 2008.23  5078.6 2010.52  5084.9 2011.01
  5093.2 2013.04    5114 2014.62    5157 2015.43  5257.4 2015.08  5281.8 2015.76
#Mann= 3 ,-1 , 0
  4626.3     .12       0    5033     .07       0  5037.1     .12       0
Bank Sta=5033,5037.1
XS Rating Curve= 0 ,0
Exp/Cntr=0.3,0.1

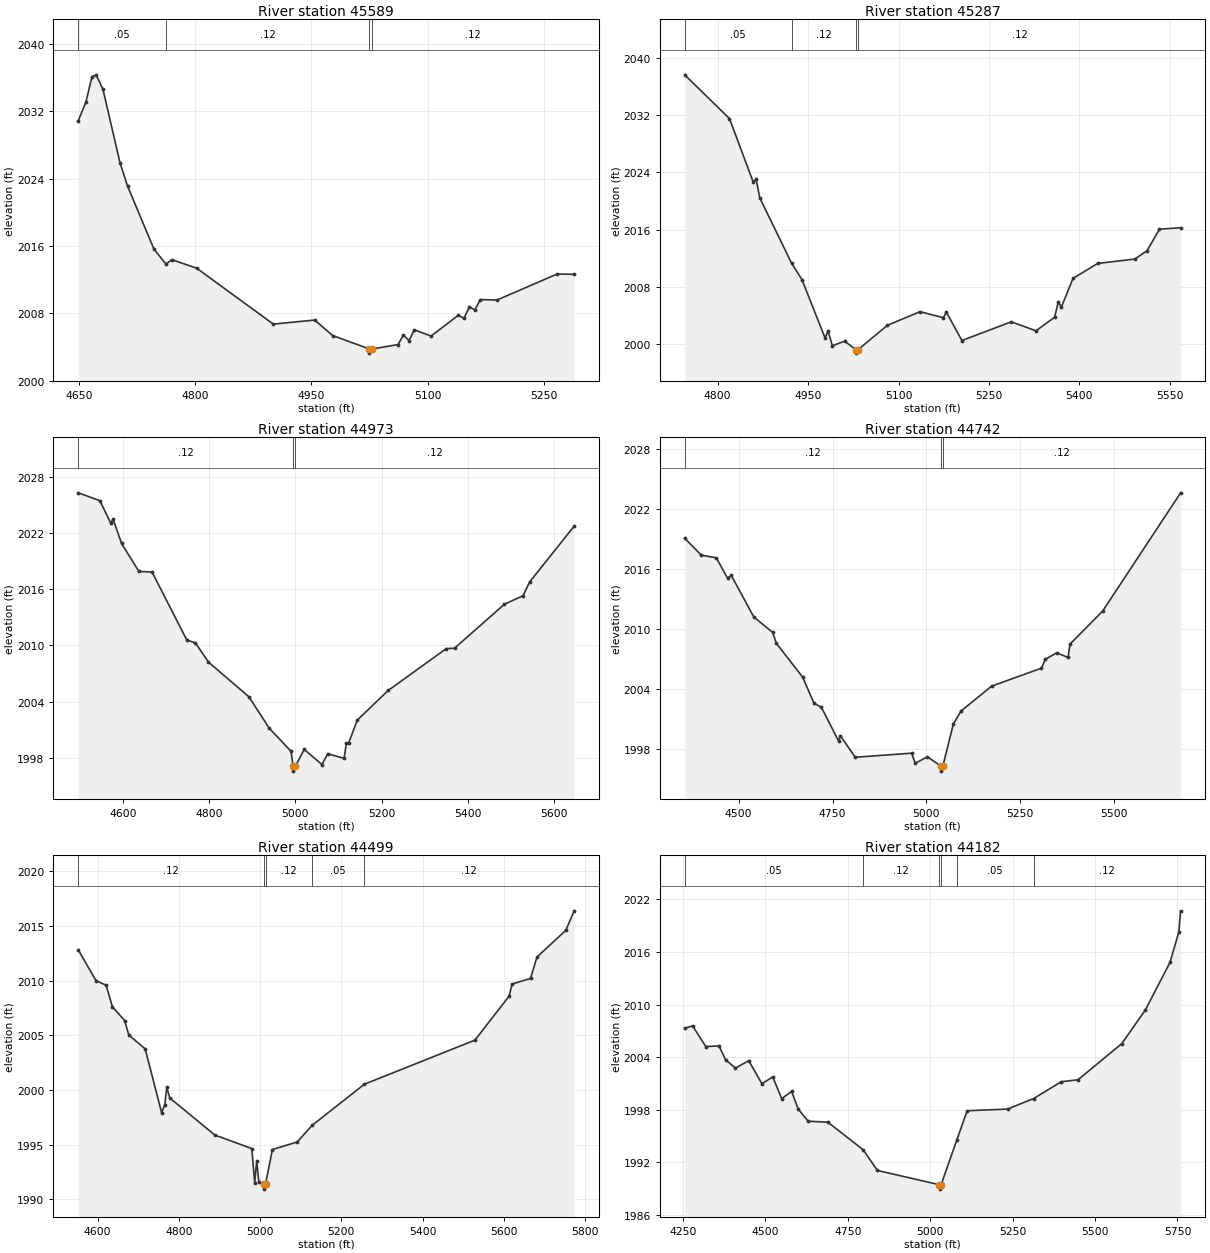
Type RM Length L Ch R = 1 ,45589   ,302,302,302
BEGIN DESCRIPTION:
Elm 01 91 45589.47
END DESCRIPTION:
XS GIS Cut Line= 3
      1602985.99      6783901.29      1603303.73      6783756.31
      1603517.26      6783559.27
#Sta/Elev= 30
  4649.2 2030.86  4659.1 2033.07  4666.9 2036.09  4672.4 2036.32  4681.1  2034.6
  4703.1 2025.88    4713 2023.07    4747  2015.6  4762.4 2013.84    4770 2014.36
    4802 2013.35  4900.9 2006.71  4954.3 2007.19  4977.4 2005.35  5024.6 2003.76
  5024.9 2003.26  5028.8 2003.76  5061.9 2004.28  5068.7 2005.42    5076 2004.75
  5082.8 2006.03  5104.4 2005.29  5139.5 2007.75  5146.9  2007.4  5153.7 2008.74
  5161.1 2008.41  5167.9 2009.62  5189.5 2009.57  5267.1 2012.66    5289 2012.62
#Mann= 4 ,-1 , 0
  4649.2     .05       0  4762.4     .12       0  5024.6     .07       0
  5028.8     .12       0
Bank Sta=5024.6,5028.8
XS Rating Curve= 0 ,0
Exp/Cntr=0.3,0.1

Type RM Length L Ch R = 1 ,45287   ,314,314,314
BEGIN DESCRIPTION:
Elm 01 91 45286.61
END DESCRIPTION:
XS GIS Cut Line= 3
      1602950.95      6784042.94      1603204.39      6784021.42
      1603759.29      6783899.88
#Sta/Elev= 30
  4745.4 2037.64  4819.7 2031.52  4858.9 2022.68  4863.9 2023.02  4869.9 2020.45
  4922.6 2011.31  4940.1 2008.97  4978.2 2000.84  4983.2 2001.83  4990.3 1999.75
  5010.6 2000.41    5029 1999.23  5029.3 1998.73  5033.2 1999.23  5081.5 2002.62
  5135.6 2004.52  5174.3 2003.69  5179.4 2004.46  5205.1 2000.49    5287 2003.11
    5328 2001.85  5358.7 2003.74    5365 2005.88  5370.1 2005.17  5389.4 2009.18
  5430.3 2011.27  5491.8 2011.88  5512.2 2013.05  5532.7 2016.06  5567.8 2016.26
#Mann= 4 ,-1 , 0
  4745.4     .05       0  4922.6     .12       0    5029     .07       0
  5033.2     .12       0
Bank Sta=5029,5033.2
XS Rating Curve= 0 ,0
Exp/Cntr=0.3,0.1

Type RM Length L Ch R = 1 ,44973   ,231,231,231
BEGIN DESCRIPTION:
Elm 01 91 44973.11
END DESCRIPTION:
XS GIS Cut Line= 3
      1602885.31       6784282.6      1603384.44      6784219.23
      1604015.55      6784076.86
#Sta/Elev= 30
  4496.3  2026.3  4546.4 2025.47    4572 2023.04  4577.1  2023.5  4596.8  2020.9
  4637.1  2017.9  4667.4 2017.85    4748 2010.59  4768.2 2010.27  4798.4 2008.22
  4892.1 2004.52  4939.5 2001.15  4989.9  1998.7  4994.7 1997.08  4995.1 1996.58
  4999.7 1997.08  5020.5  1998.9  5061.5 1997.28    5075 1998.44  5112.8 1997.94
  5118.3 1999.58  5123.4 1999.57  5143.5 2002.03  5215.3  2005.2  5349.8 2009.66
  5369.1 2009.71  5484.6  2014.4  5527.8 2015.31  5543.3 2016.79  5646.4 2022.74
#Mann= 3 ,-1 , 0
  4496.3     .12       0  4994.7     .07       0  4999.7     .12       0
Bank Sta=4994.7,4999.7
XS Rating Curve= 0 ,0
Exp/Cntr=0.3,0.1

Type RM Length L Ch R = 1 ,44742   ,243,243,243
BEGIN DESCRIPTION:
Elm 01 91 44742
END DESCRIPTION:
XS GIS Cut Line= 3
      1602860.83       6784421.3      1603504.26      6784408.28
      1604168.32      6784274.81
#Sta/Elev= 30
  4356.2  2019.1  4400.4  2017.4  4440.4 2017.13  4470.4 2015.09  4480.4 2015.36
  4540.4 2011.19  4590.4 2009.65  4600.4 2008.55  4670.4 2005.16  4700.4 2002.56
  4720.4 2002.13  4765.9 1998.76  4770.9 1999.28  4810.5 1997.12  4960.5 1997.53
  4970.5 1996.51  5002.7 1997.17  5038.8 1996.23  5039.2 1995.73  5043.8 1996.23
  5071.9 2000.47  5092.3 2001.76  5173.8 2004.26  5306.5 2006.06  5316.7 2006.95
  5347.3  2007.6  5377.3 2007.13  5382.4 2008.47  5469.7  2011.8  5677.1 2023.65
#Mann= 3 ,-1 , 0
  4356.2     .12       0  5038.8     .07       0  5043.8     .12       0
Bank Sta=5038.8,5043.8
XS Rating Curve= 0 ,0
Exp/Cntr=0.3,0.1

Type RM Length L Ch R = 1 ,44499   ,317,317,317
BEGIN DESCRIPTION:
Elm 01 91 44498.69
END DESCRIPTION:
XS GIS Cut Line= 3
      1602961.72      6784553.68      1603404.43      6784614.44
       1604165.1      6784473.38
#Sta/Elev= 30
  4552.5 2012.81  4596.2 2009.99  4621.2 2009.57  4636.6  2007.6  4666.8 2006.34
  4676.9 2005.02  4717.3 2003.75  4757.7 1997.93  4765.4 1998.61  4770.5 2000.23
  4777.9 1999.26  4888.9 1995.87  4979.7 1994.64  4986.8 1991.53  4991.8 1993.53
  4997.1 1991.54  5008.7 1991.43  5009.1 1990.93  5013.7 1991.43  5030.4 1994.55
  5091.5 1995.24  5128.2 1996.76  5256.7 2000.52  5528.8 2004.55  5612.9 2008.57
  5620.3 2009.68  5665.7 2010.19  5681.4 2012.14  5752.6 2014.59    5773 2016.37
#Mann= 5 ,-1 , 0
  4552.5     .12       0  5008.7     .07       0  5013.7     .12       0
  5128.2     .05       0  5256.7     .12       0
Bank Sta=5008.7,5013.7
XS Rating Curve= 0 ,0
Exp/Cntr=0.3,0.1

Type RM Length L Ch R = 1 ,44182   ,218,218,218
BEGIN DESCRIPTION:
Elm 01 91 44182.27
END DESCRIPTION:
XS GIS Cut Line= 3
      1602860.99      6784822.34      1603604.52      6784852.29
      1604350.27      6784706.52
#Sta/Elev= 30
  4255.6 2007.29  4279.6 2007.56  4319.7  2005.2  4359.7 2005.27  4379.7 2003.69
  4409.7 2002.74  4449.8 2003.59  4489.8 2000.96  4522.7 2001.73  4549.9 1999.25
  4579.9 2000.08  4599.9 1998.06  4629.9 1996.68    4690 1996.56  4796.7 1993.42
  4840.1 1991.05  5028.3 1989.42  5028.6 1988.92  5033.3 1989.42    5081 1994.55
  5112.3 1997.87  5234.6 1998.06  5313.5 1999.26  5397.6 2001.18  5448.6 2001.41
    5581 2005.53  5652.3 2009.36  5727.3  2014.8  5754.2 2018.29  5759.6  2020.7
#Mann= 6 ,-1 , 0
  4255.6     .05       0  4796.7     .12       0  5028.3     .07       0
  5033.3     .12       0    5081     .05       0  5313.5     .12       0
Bank Sta=5028.3,5033.3
XS Rating Curve= 0 ,0
Exp/Cntr=0.3,0.1

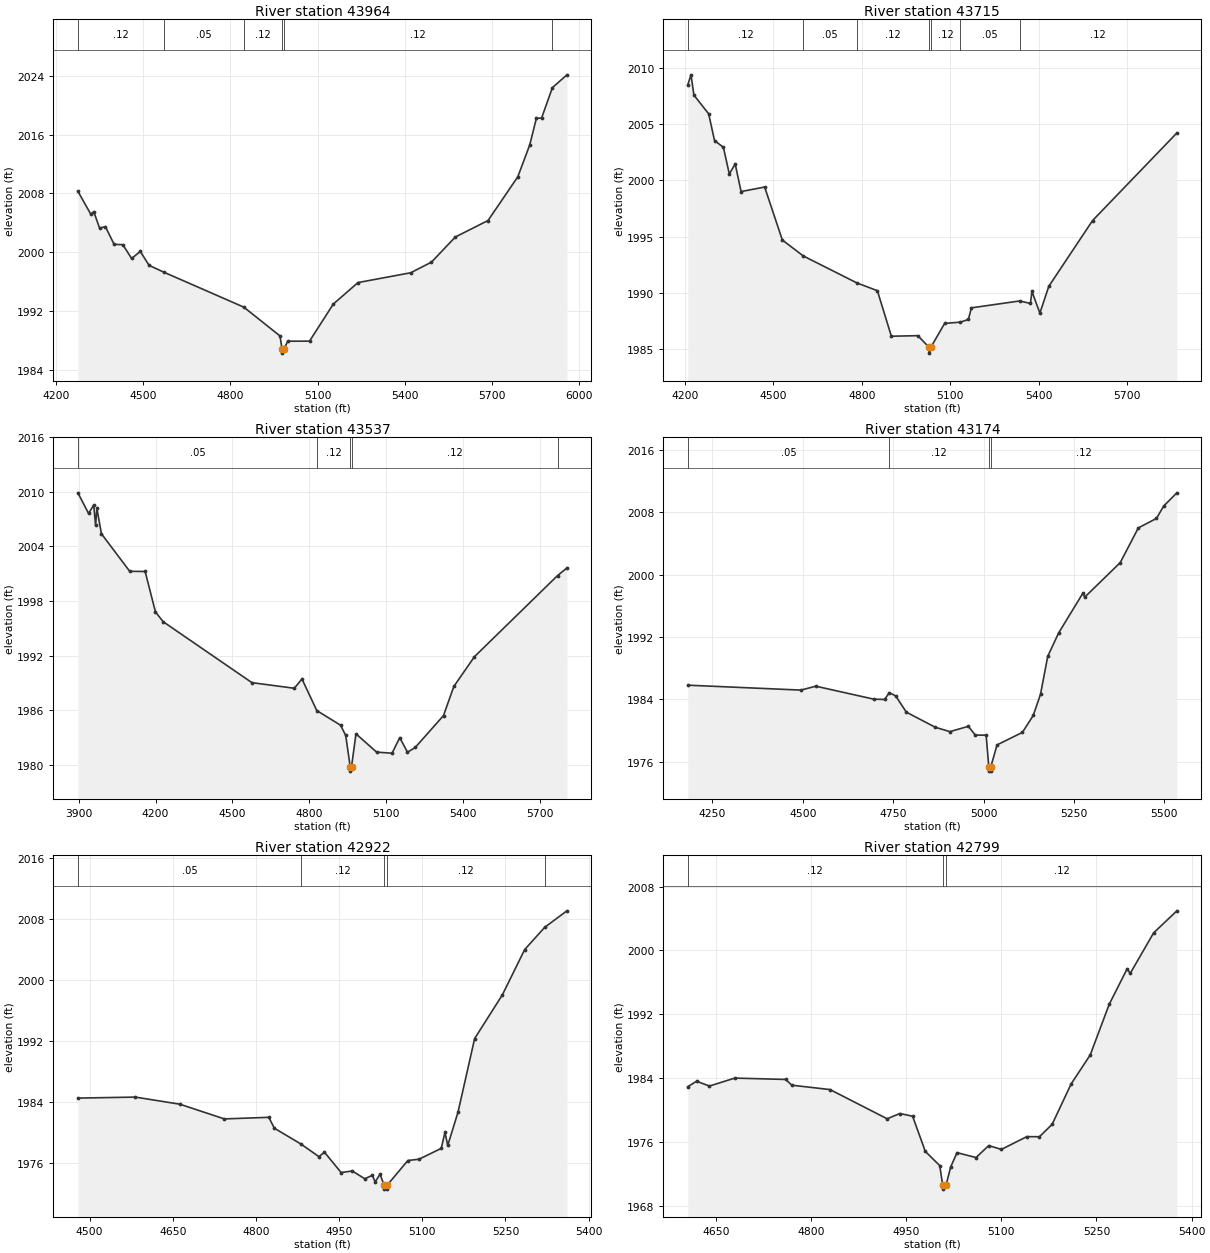
Type RM Length L Ch R = 1 ,43964   ,249,249,249
BEGIN DESCRIPTION:
Elm 01 91 43964.41
END DESCRIPTION:
XS GIS Cut Line= 3
      1602780.35      6785007.24      1603504.26      6785033.28
      1604440.21      6784830.21
#Sta/Elev= 30
  4275.6 2008.29  4320.3 2005.15  4330.3 2005.52  4350.3 2003.27  4370.3 2003.48
  4400.3 2001.07  4430.3 2001.03  4460.4 1999.15  4490.4 2000.11  4520.4 1998.22
  4573.1 1997.26  4846.3 1992.54  4970.7 1988.63  4978.2 1986.79  4978.6 1986.29
  4983.3 1986.79  4997.8 1987.91  5072.4 1987.92  5154.2 1992.96  5239.2 1995.88
  5420.3 1997.21  5491.9 1998.66  5573.8 2002.07  5686.3 2004.31  5788.7 2010.25
  5829.6 2014.56  5852.7 2018.21  5870.5 2018.23  5907.8 2022.37  5957.7 2024.11
#Mann= 6 ,-1 , 0
  4275.6     .12       0  4573.1     .05       0  4846.3     .12       0
  4978.2     .07       0  4983.3     .12       0  5907.8     .05       0
Bank Sta=4978.2,4983.3
XS Rating Curve= 0 ,0
Exp/Cntr=0.3,0.1

Type RM Length L Ch R = 1 ,43715   ,178,178,178
BEGIN DESCRIPTION:
Elm 01 91 43715.19
END DESCRIPTION:
XS GIS Cut Line= 3
       1602664.2      6785244.65      1603452.41      6785267.22
      1604315.27      6785142.22
#Sta/Elev= 30
  4209.3 2008.49  4220.1 2009.37  4230.1 2007.57  4280.1 2005.91  4300.1 2003.53
  4330.1 2002.94  4350.2 2000.57  4370.2 2001.46  4390.2 1999.01  4470.2 1999.41
  4530.2 1994.71  4601.6 1993.29  4783.5  1990.9  4852.9 1990.21  4900.4 1986.17
  4990.4 1986.22  5028.9 1985.17  5029.3 1984.67  5034.1 1985.17  5081.3 1987.31
  5135.1 1987.42  5161.9 1987.66  5172.2 1988.69    5336  1989.3  5372.6 1989.08
  5377.7 1990.15  5404.6 1988.22  5434.9  1990.6  5583.3 1996.43  5869.7 2004.21
#Mann= 7 ,-1 , 0
  4209.3     .12       0  4601.6     .05       0  4783.5     .12       0
  5028.9     .07       0  5034.1     .12       0  5135.1     .05       0
    5336     .12       0
Bank Sta=5028.9,5034.1
XS Rating Curve= 0 ,0
Exp/Cntr=0.3,0.1

Type RM Length L Ch R = 1 ,43537   ,363,363,363
BEGIN DESCRIPTION:
Elm 01 91 43536.51
END DESCRIPTION:
XS GIS Cut Line= 3
      1602433.35       6785487.7      1603537.48      6785414.79
      1604334.32      6785348.82
#Sta/Elev= 30
  3897.4 2009.89  3939.1 2007.62  3959.2 2008.56  3966.5 2006.31  3971.5 2008.19
  3989.2 2005.39  4099.5 2001.26  4159.6 2001.24  4199.7  1996.8  4229.8 1995.72
  4575.7 1989.02  4740.9  1988.4  4770.9 1989.42  4828.5 1985.95  4921.3 1984.34
  4941.3 1983.21  4958.8 1979.79  4959.2 1979.29    4964 1979.79  4981.4 1983.39
  5061.7 1981.38  5121.9 1981.26    5152 1982.97  5182.1 1981.37  5212.2 1981.89
  5322.5  1985.4  5362.7  1988.6    5443 1991.87  5766.9 2000.79  5803.5 2001.63
#Mann= 5 ,-1 , 0
  3897.4     .05       0  4828.5     .12       0  4958.8     .07       0
    4964     .12       0  5766.9     .05       0
Bank Sta=4958.8,4964
XS Rating Curve= 0 ,0
Exp/Cntr=0.3,0.1

Type RM Length L Ch R = 1 ,43174   ,252,252,252
BEGIN DESCRIPTION:
Elm 01 91 43174.33
END DESCRIPTION:
XS GIS Cut Line= 3
      1602981.89      6785683.89      1603796.16      6785630.07
       1604331.3      6785597.16
#Sta/Elev= 30
  4182.3 1985.83    4495  1985.2  4536.2  1985.7  4696.5 1984.04  4726.6    1984
  4739.2 1984.87  4756.7 1984.47  4786.7 1982.37  4866.9 1980.43    4907 1979.88
    4958 1980.56  4977.1 1979.44  5007.2 1979.42  5014.6 1975.32    5015 1974.82
  5019.4 1974.82  5019.8 1975.32  5037.3 1978.18  5107.4 1979.78  5137.4 1981.95
  5157.5 1984.67  5177.5 1989.53  5207.6 1992.52  5274.6 1997.61  5279.6  1997.1
  5377.9 2001.53    5428 2005.98  5478.1 2007.19  5498.1 2008.78  5534.5 2010.47
#Mann= 4 ,-1 , 0
  4182.3     .05       0  4739.2     .12       0  5014.6     .07       0
  5019.8     .12       0
Bank Sta=5014.6,5019.8
XS Rating Curve= 0 ,0
Exp/Cntr=0.3,0.1

Type RM Length L Ch R = 1 ,42922   ,123,123,123
BEGIN DESCRIPTION:
Elm 01 91 42922.1
END DESCRIPTION:
XS GIS Cut Line= 3
      1603261.65       6785774.6      1603783.75      6785813.66
      1604140.95      6785786.38
#Sta/Elev= 30
    4479 1984.52  4582.6 1984.65  4662.9 1983.72  4743.1 1981.79  4823.3    1982
  4833.3 1980.57    4881 1978.51  4913.6 1976.85  4923.6 1977.43  4953.7 1974.76
  4973.7 1974.97  4996.3 1973.95    5010  1974.4    5015 1973.53  5023.9 1974.55
  5031.2 1973.09  5031.7 1972.59  5036.1 1972.59  5036.5 1973.09    5074 1976.34
  5094.1 1976.51  5134.2 1977.93  5140.9 1980.03  5145.9 1978.32  5164.3 1982.64
  5194.4 1992.32  5244.5 1998.06  5284.6 2003.98  5320.9 2006.91  5360.8 2009.06
#Mann= 5 ,-1 , 0
    4479     .05       0    4881     .12       0  5031.2     .07       0
  5036.5     .12       0  5320.9     .05       0
Bank Sta=5031.2,5036.5
XS Rating Curve= 0 ,0
Exp/Cntr=0.3,0.1

Type RM Length L Ch R = 1 ,42799   ,353,353,353
BEGIN DESCRIPTION:
Elm 01 91 42799.49
END DESCRIPTION:
XS GIS Cut Line= 3
      1603311.08      6785925.64      1603705.62      6785906.11
      1604081.58      6785902.22
#Sta/Elev= 30
  4605.7 1982.92  4619.6 1983.61  4639.7    1983  4679.7    1984  4759.8 1983.83
  4769.8 1983.11  4829.9 1982.56    4920  1978.9    4940 1979.56  4960.1 1979.22
  4980.1 1974.81  5002.9 1973.03  5007.5 1970.58  5007.9 1970.08  5012.8 1970.58
  5020.1 1972.85  5030.1 1974.65  5060.1 1974.04  5080.1 1975.54  5100.1 1975.06
  5140.1 1976.66  5160.1 1976.65  5180.1 1978.21  5210.1 1983.28  5240.1  1986.9
  5270.1 1993.26  5298.2 1997.68  5303.2 1997.13  5340.1 2002.21  5376.7 2004.97
#Mann= 3 ,-1 , 0
  4605.7     .12       0  5007.5     .07       0  5012.8     .12       0
Bank Sta=5007.5,5012.8
XS Rating Curve= 0 ,0
Exp/Cntr=0.3,0.1

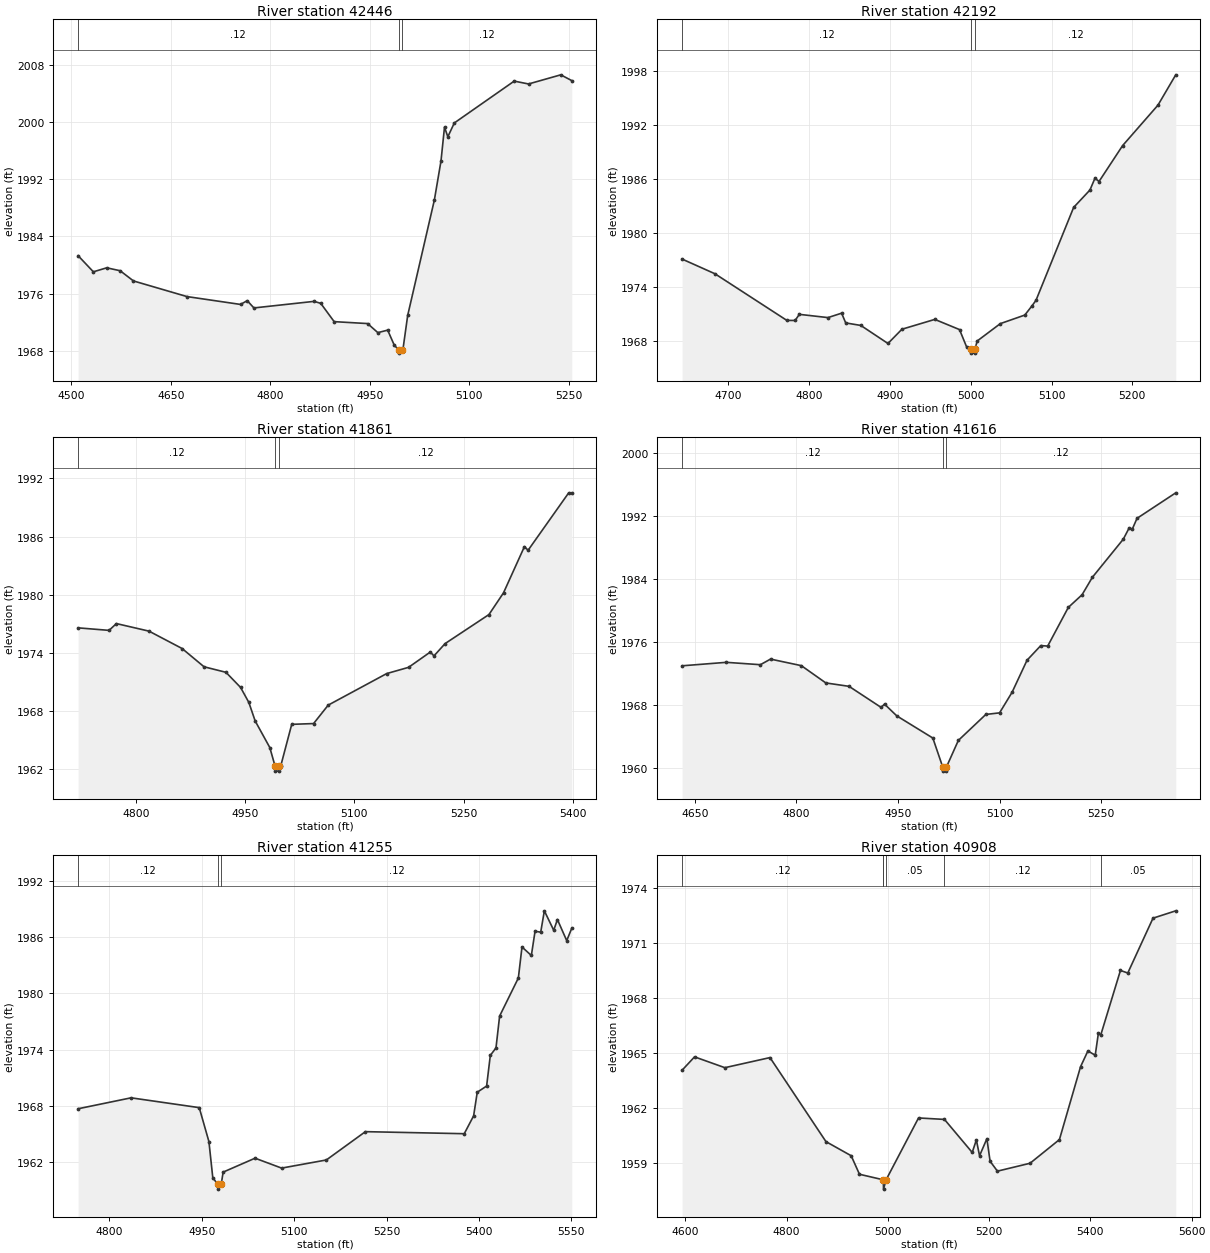
Type RM Length L Ch R = 1 ,42446   ,254,254,254
BEGIN DESCRIPTION:
Elm 01 91 42445.91
END DESCRIPTION:
XS GIS Cut Line= 3
      1603462.17      6786074.08      1603947.81      6786137.88
      1604201.55      6786158.59
#Sta/Elev= 30
  4510.3 1981.31  4533.3 1979.05  4553.5 1979.61  4573.7  1979.2  4593.8 1977.77
  4674.5 1975.58  4755.2 1974.48  4765.3 1975.01  4775.4 1973.99  4866.2 1974.91
  4876.2 1974.63  4896.4 1972.07  4946.8  1971.8  4962.3 1970.53  4977.1 1970.88
  4987.2 1968.74  4993.5 1968.16  4993.9 1967.66  4998.8 1968.16  5000.1 1968.16
  5007.3 1972.95  5047.5  1989.1  5057.5 1994.57  5062.8 1999.32  5067.8 1997.96
  5077.6  1999.9  5167.9 2005.76  5189.5 2005.36  5238.1 2006.64  5254.7 2005.83
#Mann= 3 ,-1 , 0
  4510.3     .12       0  4993.5     .07       0  4998.8     .12       0
Bank Sta=4993.5,4998.8
XS Rating Curve= 0 ,0
Exp/Cntr=0.3,0.1

Type RM Length L Ch R = 1 ,42192   ,331,331,331
BEGIN DESCRIPTION:
Elm 01 91 42192.22
END DESCRIPTION:
XS GIS Cut Line= 3
      1603457.55       6786275.9      1603807.83      6786342.31
      1604060.26      6786376.14
#Sta/Elev= 30
  4642.6  1977.1  4683.3 1975.47  4772.3  1970.3  4782.5 1970.29  4787.8 1970.97
  4823.2 1970.61  4840.1  1971.1  4845.2 1970.02  4863.9 1969.74  4897.5 1967.74
  4914.8 1969.32  4955.5 1970.41  4986.1 1969.28  4995.1 1967.31  5000.2 1967.17
  5000.6 1966.67  5005.1 1966.67  5005.5 1967.17  5007.9 1968.01  5036.6 1969.94
  5066.9 1970.89  5075.8 1971.91  5080.8 1972.53  5127.4 1982.83  5147.6 1984.76
  5153.8 1986.07  5158.8  1985.7    5188 1989.68  5231.8 1994.17  5253.8 1997.53
#Mann= 3 ,-1 , 0
  4642.6     .12       0  5000.2     .07       0  5005.5     .12       0
Bank Sta=5000.2,5005.5
XS Rating Curve= 0 ,0
Exp/Cntr=0.3,0.1

Type RM Length L Ch R = 1 ,41861   ,245,245,245
BEGIN DESCRIPTION:
Elm 01 91 41860.61
END DESCRIPTION:
XS GIS Cut Line= 3
      1603332.57      6786510.27      1603609.92      6786489.44
      1604008.37      6786458.19
#Sta/Elev= 30
  4720.7 1976.59  4763.2 1976.33  4773.3 1977.03  4818.1 1976.25  4863.5 1974.46
  4893.6 1972.58  4923.7 1972.01  4943.8 1970.45  4955.1 1968.91  4963.8    1967
  4983.9 1964.26  4991.2 1962.33  4991.6 1961.83  4996.1 1961.83  4996.5 1962.33
  4998.8 1962.33    5014 1966.65    5044 1966.73  5064.1 1968.63  5144.4 1971.88
  5174.4 1972.52  5204.3  1974.1  5209.3  1973.7  5224.6 1974.97  5284.8 1977.96
  5304.8  1980.2  5333.5 1984.96  5338.5 1984.58  5394.3  1990.5  5398.5  1990.5
#Mann= 3 ,-1 , 0
  4720.7     .12       0  4991.2     .07       0  4996.5     .12       0
Bank Sta=4991.2,4996.5
XS Rating Curve= 0 ,0
Exp/Cntr=0.3,0.1

Type RM Length L Ch R = 1 ,41616   ,361,361,361
BEGIN DESCRIPTION:
Elm 01 91 41616.43
END DESCRIPTION:
XS GIS Cut Line= 3
       1603340.1      6786748.77      1603705.73      6786704.29
      1604061.32       6786641.6
#Sta/Elev= 30
    4631 1972.99  4696.4 1973.43  4746.7 1973.13  4761.7 1973.84  4807.2 1973.01
  4843.4 1970.82  4877.7 1970.39  4925.1 1967.72  4930.1 1968.14  4948.2 1966.65
  5001.5 1963.84  5016.2 1960.15  5016.6 1959.65  5021.1 1959.65  5021.5 1960.15
  5039.2 1963.54  5079.8 1966.83  5100.1 1967.03  5118.6 1969.64  5140.7  1973.7
    5161 1975.55  5171.2 1975.49  5201.7 1980.39    5222 1981.99  5237.2  1984.2
  5282.9 1989.03  5291.3 1990.41  5296.4 1990.34  5303.2 1991.67  5360.4  1994.9
#Mann= 3 ,-1 , 0
    4631     .12       0  5016.2     .07       0  5021.5     .12       0
Bank Sta=5016.2,5021.5
XS Rating Curve= 0 ,0
Exp/Cntr=0.3,0.1

Type RM Length L Ch R = 1 ,41255   ,347,347,347
BEGIN DESCRIPTION:
Elm 01 91 41255.18
END DESCRIPTION:
XS GIS Cut Line= 3
        1603446.      6787110.55       1603675.2      6787006.37
      1604136.97      6786708.65
#Sta/Elev= 30
  4749.4 1967.66  4835.4 1968.83    4946 1967.78  4961.7 1964.15    4968 1960.28
  4976.3 1959.56  4976.7 1959.06  4981.6 1959.56  4984.8 1960.88  5036.6 1962.37
  5079.7 1961.31  5152.3 1962.18  5215.7 1965.21  5376.1 1964.99  5391.3  1966.9
  5397.2 1969.43  5412.4 1970.09  5418.4 1973.37  5427.6 1974.17  5433.5 1977.58
  5463.9 1981.65  5469.8 1984.97    5485 1984.06    5491 1986.65  5500.2 1986.56
  5506.1 1988.84  5521.3 1986.76  5527.3 1987.91  5542.4 1985.65  5550.6 1986.98
#Mann= 3 ,-1 , 0
  4749.4     .12       0  4976.3     .07       0  4981.6     .12       0
Bank Sta=4976.3,4981.6
XS Rating Curve= 0 ,0
Exp/Cntr=0.3,0.1

Type RM Length L Ch R = 1 ,40908   ,428,428,428
BEGIN DESCRIPTION:
Elm 01 91 40907.7
END DESCRIPTION:
XS GIS Cut Line= 3
      1603590.08      6787375.41      1603949.44      6787187.92
      1604296.65      6786736.54
#Sta/Elev= 30
  4593.8 1964.08  4618.4 1964.81  4678.3 1964.22  4767.4 1964.77  4877.9 1960.19
  4927.7 1959.42  4944.1 1958.41  4990.8 1958.11  4991.2  1958.1  4991.6  1957.6
  4996.5  1958.1  5060.7 1961.48  5111.9  1961.4  5166.7  1959.6  5174.9 1960.28
  5181.2 1959.42  5195.7 1960.35    5202 1959.12  5216.5 1958.58  5280.9 1959.01
  5338.9  1960.3  5380.6 1964.27  5395.1 1965.13  5409.6  1964.9  5415.9 1966.11
  5420.4 1965.99  5459.4 1969.52  5473.9 1969.38  5523.7 1972.37  5568.6 1972.77
#Mann= 6 ,-1 , 0
  4593.8     .12       0  4990.8     .05       0  4991.2     .05       0
  4996.5     .05       0  5111.9     .12       0  5420.4     .05       0
Bank Sta=4991.2,4996.5
XS Rating Curve= 0 ,0
Exp/Cntr=0.3,0.1

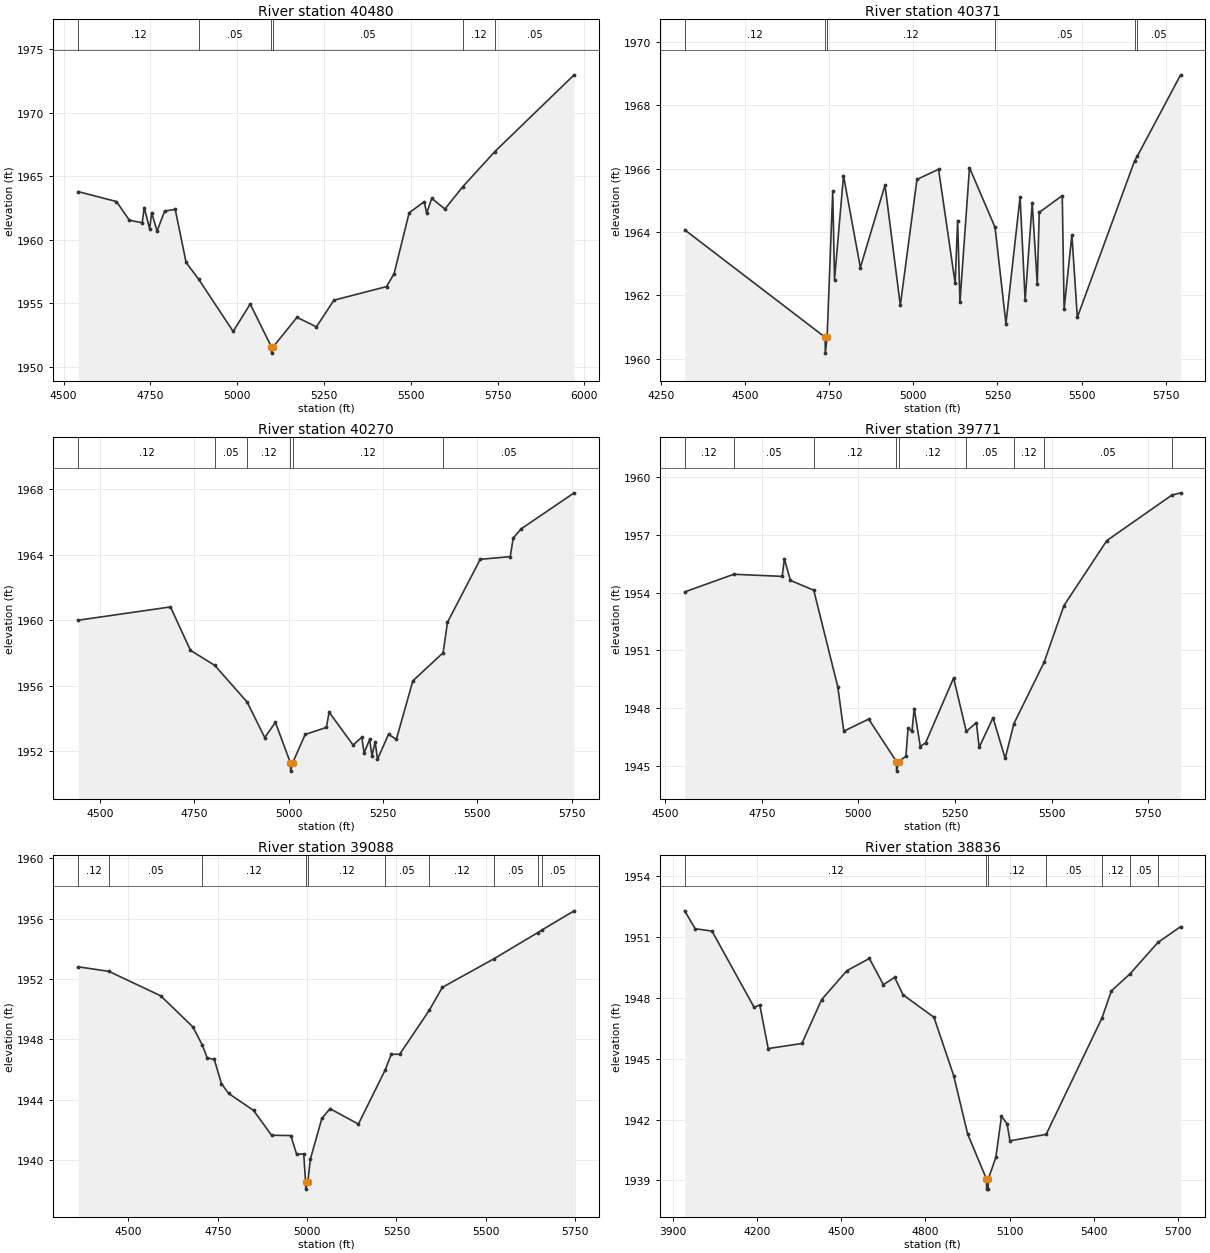
Type RM Length L Ch R = 1 ,40480   ,109,109,109
BEGIN DESCRIPTION:
Elm 01 91 40480.11
END DESCRIPTION:
XS GIS Cut Line= 6
      1603784.35      6787337.45      1604032.99      6787484.18
      1604119.57      6787474.38      1604194.23      6787439.65
      1604444.23      6787151.46      1604730.32      6786636.49
#Sta/Elev= 30
    4542 1963.78  4652.2    1963  4689.3 1961.53  4726.4 1961.33  4732.2 1962.52
  4747.8 1960.85  4753.6 1962.12  4769.3 1960.67  4790.7 1962.24  4821.4 1962.39
  4852.9  1958.2  4888.8 1956.89  4988.4 1952.77  5037.5 1954.93  5098.5 1951.56
  5098.9 1951.06  5103.8 1951.56  5172.3 1953.88  5228.3 1953.13  5278.7 1955.23
  5430.2  1956.3    5452 1957.31  5495.4 1962.11  5538.9 1962.99  5545.8 1962.08
  5560.6 1963.25  5598.4 1962.41    5650 1964.17  5742.5 1966.94  5970.8 1972.98
#Mann= 6 ,-1 , 0
    4542     .12       0  4888.8     .05       0  5098.5     .05       0
  5103.8     .05       0    5650     .12       0  5742.5     .05       0
Bank Sta=5098.5,5103.8
XS Rating Curve= 0 ,0
Exp/Cntr=0.3,0.1

Type RM Length L Ch R = 1 ,40371   ,101,101,101
BEGIN DESCRIPTION:
Elm 01 91 40370.8
END DESCRIPTION:
XS GIS Cut Line= 6
      1603651.55      6787388.24      1604074.44      6787545.56
      1604206.38      6787536.88      1604435.55      6787351.11
      1604560.55      6787165.35      1604713.31      6786828.57
#Sta/Elev= 30
  4320.8 1964.07  4738.1 1960.68  4738.6 1960.18  4743.9 1960.68  4760.6 1965.28
    4766  1962.5  4792.6 1965.78  4842.7 1962.88  4915.9 1965.48  4961.4 1961.69
  5010.9 1965.66    5075 1965.98  5124.3 1962.39  5131.7 1964.36  5138.5 1961.78
  5166.9 1966.03  5242.8 1964.15  5275.2 1961.11  5317.2 1965.11  5332.2 1961.85
  5353.2 1964.91  5368.2 1962.37  5374.2 1964.62  5442.5 1965.15    5448 1961.57
  5471.1 1963.91  5487.3 1961.31  5657.2 1966.24  5665.8  1966.4  5794.1 1968.96
#Mann= 6 ,-1 , 0
  4320.8     .12       0  4738.1     .07       0  4743.9     .12       0
  5242.8     .05       0  5657.2     .12       0  5665.8     .05       0
Bank Sta=4738.1,4743.9
XS Rating Curve= 0 ,0
Exp/Cntr=0.3,0.1

Type RM Length L Ch R = 1 ,40270   ,499,499,499
BEGIN DESCRIPTION:
Elm 01 91 40269.86
END DESCRIPTION:
XS GIS Cut Line= 6
      1603859.18       6787677.5      1604234.16      6787608.06
      1604355.69      6787543.82      1604381.73      6787512.57
      1604638.67      6787168.82      1604817.46      6786896.29
#Sta/Elev= 30
  4442.2    1960  4686.8 1960.81  4739.7 1958.16  4804.2 1957.24  4889.9    1955
  4936.7 1952.83  4964.9 1953.76  5004.8 1951.28  5005.3 1950.78  5010.6 1951.28
  5043.8 1953.02    5100 1953.45  5107.3 1954.38  5170.9 1952.37  5193.8 1952.85
  5200.1 1951.89  5214.7 1952.72  5220.9 1951.71  5229.3 1952.58  5235.5  1951.5
  5264.7 1953.03  5285.5 1952.72  5329.3  1956.3  5409.5 1958.01    5421 1959.87
  5507.9 1963.72  5587.3 1963.88  5595.3 1965.02  5616.4 1965.58  5756.8 1967.78
#Mann= 6 ,-1 , 0
  4442.2     .12       0  4804.2     .05       0  4889.9     .12       0
  5004.8     .07       0  5010.6     .12       0  5409.5     .05       0
Bank Sta=5004.8,5010.6
XS Rating Curve= 0 ,0
Exp/Cntr=0.3,0.1

Type RM Length L Ch R = 1 ,39771   ,683,683,683
BEGIN DESCRIPTION:
Elm 01 91 39771.35
END DESCRIPTION:
XS GIS Cut Line= 3
      1604077.78      6788124.77      1604464.05      6787894.75
      1605186.66      6787478.11
#Sta/Elev= 30
  4550.3 1954.04  4677.2 1954.96  4802.6 1954.85  4808.4 1955.76    4824 1954.64
  4884.4 1954.13  4946.6  1949.1  4962.2 1946.79  5026.6 1947.42  5098.4 1945.21
  5098.9 1944.71  5104.2 1945.21  5122.8 1945.48  5128.6 1946.95  5138.6 1946.78
  5144.4 1947.97  5160.2 1945.99  5174.1 1946.19  5246.4 1949.56  5279.2 1946.78
  5305.3 1947.23  5312.6 1945.95  5348.4 1947.49  5379.9 1945.37  5402.4 1947.18
  5480.7 1950.38    5532 1953.33  5642.8 1956.71  5811.2 1959.08    5834  1959.2
#Mann= 9 ,-1 , 0
  4550.3     .12       0  4677.2     .05       0  4884.4     .12       0
  5098.4     .07       0  5104.2     .12       0  5279.2     .05       0
  5402.4     .12       0  5480.7     .05       0  5811.2     .12       0
Bank Sta=5098.4,5104.2
XS Rating Curve= 0 ,0
Exp/Cntr=0.3,0.1

Type RM Length L Ch R = 1 ,39088   ,252,252,252
BEGIN DESCRIPTION:
Elm 01 91 39088.03
END DESCRIPTION:
XS GIS Cut Line= 3
       1604214.5      6788228.95      1604856.84      6788254.99
      1605586.01      6788103.08
#Sta/Elev= 30
  4359.4 1952.81  4445.2 1952.51  4590.1 1950.89  4680.2 1948.83  4706.8 1947.62
  4720.2 1946.78  4740.2 1946.67  4760.2 1945.07  4780.2 1944.42  4850.3 1943.29
  4900.3 1941.65  4954.3 1941.63  4970.4  1940.4  4990.4 1940.41  4995.6 1938.58
  4996.1 1938.08  5002.1 1938.58  5008.8 1940.05  5041.2 1942.77  5063.9 1943.41
  5143.4 1942.39  5217.8 1945.95  5235.3 1947.01    5259 1947.02  5341.4 1949.92
  5378.3 1951.45  5523.2 1953.35  5644.7 1955.07  5658.2 1955.27  5747.1 1956.52
#Mann= 10 ,-1 , 0
  4359.4     .12       0  4445.2     .05       0  4706.8     .12       0
  4995.6     .07       0  5002.1     .12       0  5217.8     .05       0
  5341.4     .12       0  5523.2     .05       0  5644.7     .12       0
  5658.2     .05       0
Bank Sta=4995.6,5002.1
XS Rating Curve= 0 ,0
Exp/Cntr=0.3,0.1

Type RM Length L Ch R = 1 ,38836   ,135,135,135
BEGIN DESCRIPTION:
Elm 01 91 38835.62
END DESCRIPTION:
XS GIS Cut Line= 3
      1603697.79      6788452.29      1604754.67      6788460.97
      1605461.05       6788413.3
#Sta/Elev= 30
  3943.3 1952.29  3980.5 1951.41  4040.5 1951.29  4190.5 1947.53  4210.5 1947.65
  4240.5  1945.5  4360.5 1945.75  4430.5 1947.91  4520.5 1949.34  4600.5 1949.94
  4650.5 1948.65  4690.5 1949.01  4720.5 1948.15  4830.5 1947.04  4900.5 1944.17
  4950.5 1941.28  5017.3 1939.07  5017.8 1938.57  5023.3 1938.57  5023.8 1939.07
  5050.7 1940.14  5070.7 1942.16  5090.8 1941.79  5100.8 1940.95  5229.7 1941.27
  5428.5 1947.01  5461.6 1948.34  5527.9 1949.18  5627.3 1950.73  5708.2 1951.51
#Mann= 7 ,-1 , 0
  3943.3     .12       0  5017.3     .07       0  5023.8     .12       0
  5229.7     .05       0  5428.5     .12       0  5527.9     .05       0
  5627.3     .12       0
Bank Sta=5017.3,5023.8
XS Rating Curve= 0 ,0
Exp/Cntr=0.3,0.1