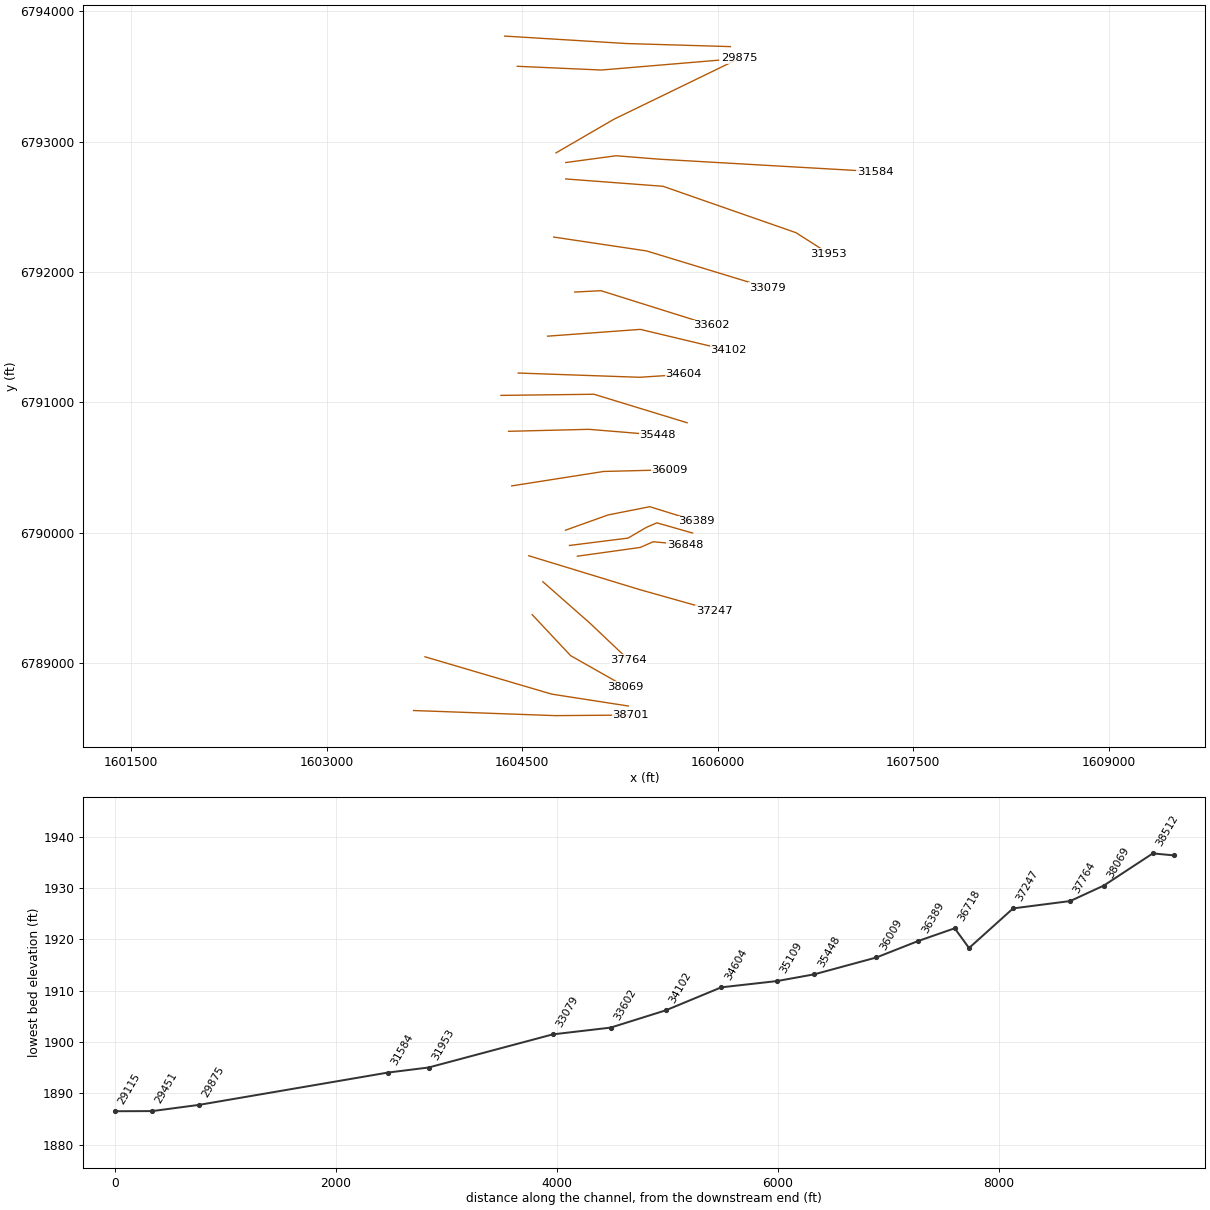
HEC-RAS study Elm 01 91.prj: Elm 01 91 Base Level Engineering

--- Elm 01 91.g01 (geometry) --- (continued)

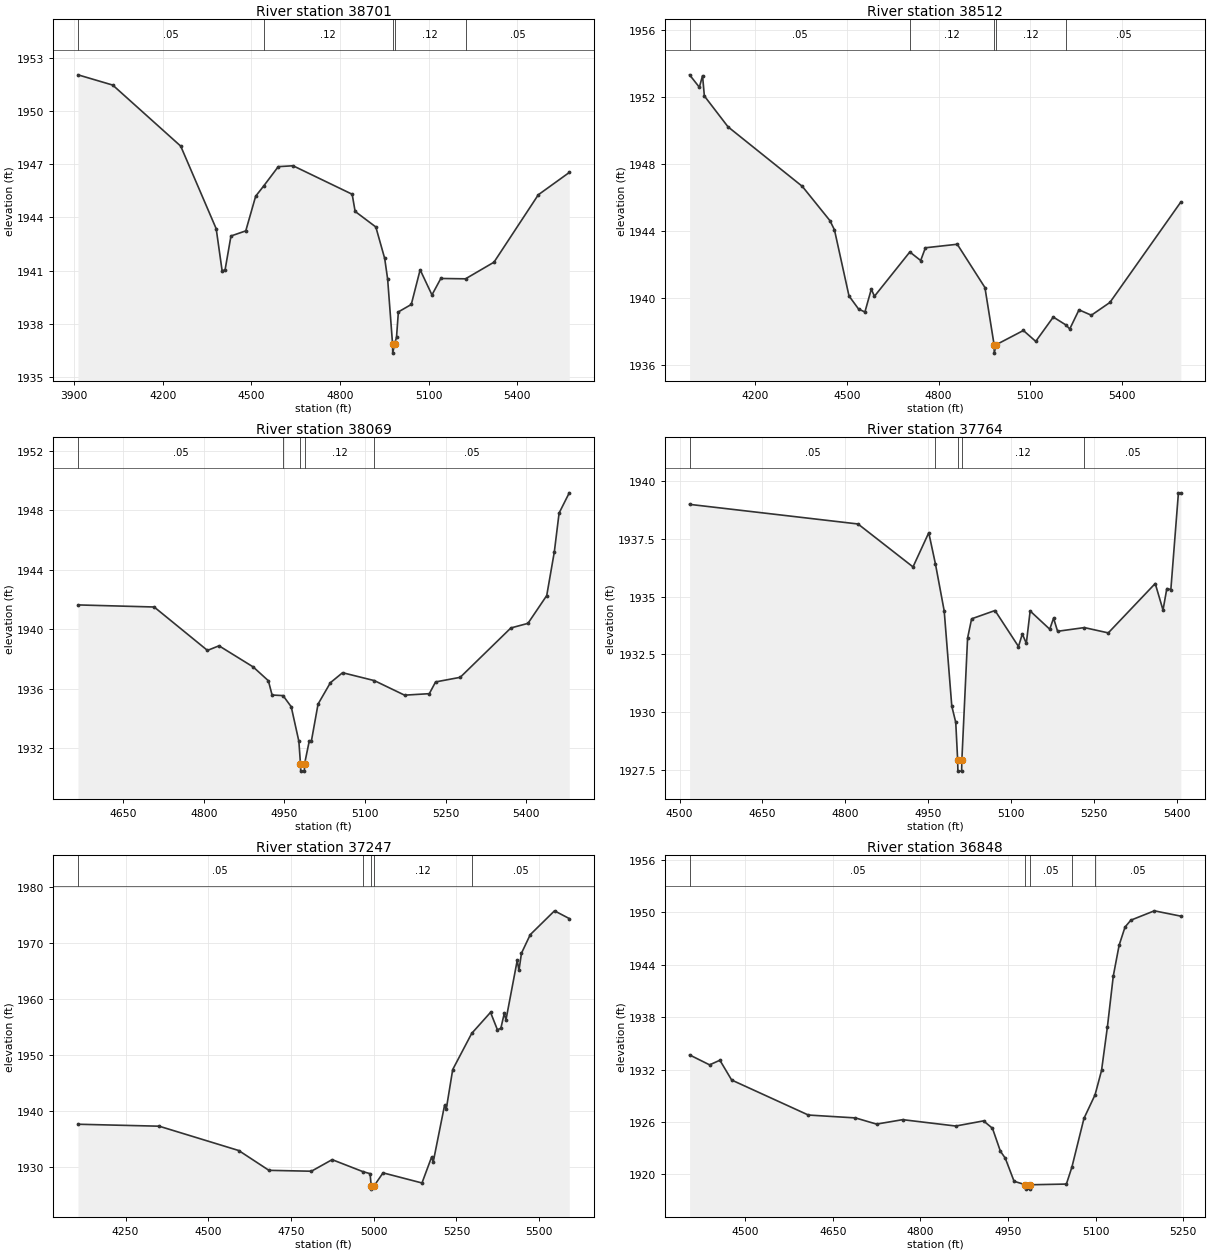
Type RM Length L Ch R = 1 ,38701   ,189,189,189
BEGIN DESCRIPTION:
Elm 01 91 38701.06
END DESCRIPTION:
XS GIS Cut Line= 3
       1603667.4      6788634.59       1604752.5      6788595.52
      1605329.78      6788599.86
#Sta/Elev= 30
  3912.8 1952.06  4030.5 1951.48  4260.6 1948.03  4380.7 1943.36  4400.7 1940.99
  4410.7 1941.03  4430.7 1942.95  4480.8 1943.24  4514.3  1945.2  4541.6 1945.78
  4590.8 1946.87  4640.9 1946.92    4841 1945.31    4851 1944.34  4921.1 1943.46
  4951.1 1941.68  4961.1 1940.51  4977.8 1936.83  4978.3 1936.33  4984.3 1936.83
  4991.1 1937.22  4997.4 1938.66  5041.1 1939.08  5071.1 1941.04  5111.1 1939.62
  5141.1 1940.55  5224.7 1940.53  5321.1 1941.47  5471.1 1945.28  5575.9 1946.54
#Mann= 5 ,-1 , 0
  3912.8     .05       0  4541.6     .12       0  4977.8     .07       0
  4984.3     .12       0  5224.7     .05       0
Bank Sta=4977.8,4984.3
XS Rating Curve= 0 ,0
Exp/Cntr=0.3,0.1

Type RM Length L Ch R = 1 ,38512   ,443,443,443
BEGIN DESCRIPTION:
Elm 01 91 38512.37
END DESCRIPTION:
XS GIS Cut Line= 3
      1603754.26       6789046.9      1604726.45      6788760.45
      1605314.52      6788669.31
#Sta/Elev= 30
  3984.8  1953.3  4016.8 1952.56  4027.3 1953.25  4033.2 1952.04  4110.7  1950.2
    4354 1946.65  4444.3 1944.61  4459.2 1944.06  4506.8 1940.12  4538.1 1939.34
  4558.9 1939.16  4579.8 1940.52  4590.2  1940.1    4706 1942.74  4741.5 1942.23
    4757 1942.99  4861.3  1943.2  4951.9 1940.62  4981.9 1937.21  4982.4 1936.71
  4988.5 1937.21  5077.8 1938.06  5118.3 1937.41  5175.7 1938.86    5217 1938.39
  5229.6 1938.15  5259.9 1939.29  5300.4 1938.97  5361.1 1939.73  5593.4 1945.72
#Mann= 5 ,-1 , 0
  3984.8     .05       0    4706     .12       0  4981.9     .07       0
  4988.5     .12       0    5217     .05       0
Bank Sta=4981.9,4988.5
XS Rating Curve= 0 ,0
Exp/Cntr=0.3,0.1

Type RM Length L Ch R = 1 ,38069   ,305,305,305
BEGIN DESCRIPTION:
Elm 01 91 38068.87
END DESCRIPTION:
XS GIS Cut Line= 3
      1604576.75      6789370.23      1604871.85      6789055.59
      1605291.43      6788817.69
#Sta/Elev= 30
  4566.2 1941.64  4707.9  1941.5    4807 1938.58  4828.5 1938.89    4892 1937.47
  4920.3 1936.54  4927.2 1935.58  4947.6 1935.54  4962.8 1934.79    4977 1932.47
    4980 1930.96  4980.5 1930.46  4987.2 1930.46  4987.7 1930.96  4996.2 1932.46
  5000.2 1932.46  5012.7 1934.97  5035.7 1936.41  5058.3 1937.08  5117.3 1936.55
  5173.6 1935.57  5219.6 1935.67  5231.3 1936.46  5277.1 1936.77  5371.3 1940.09
  5403.1  1940.4    5438 1942.27  5452.1  1945.2    5461 1947.82  5479.9 1949.18
#Mann= 5 ,-1 , 0
  4566.2     .05       0  4947.6     .12       0    4980     .07       0
  4987.7     .12       0  5117.3     .05       0
Bank Sta=4980,4987.7
XS Rating Curve= 0 ,0
Exp/Cntr=0.3,0.1

Type RM Length L Ch R = 1 ,37764   ,517,517,517
BEGIN DESCRIPTION:
Elm 01 91 37764.1
END DESCRIPTION:
XS GIS Cut Line= 3
      1604658.86       6789622.6       1605021.3      6789303.57
      1605316.41      6789023.65
#Sta/Elev= 30
    4518    1939    4823 1938.15  4922.6 1936.29  4951.1 1937.77  4963.2 1936.42
  4979.1 1934.38  4992.8 1930.26    5000 1929.55  5003.4 1927.94  5003.9 1927.44
  5010.6 1927.44  5011.1 1927.94  5021.4  1933.2  5028.7 1934.04  5071.1  1934.4
  5113.6 1932.84  5120.5 1933.38  5127.8 1932.98  5134.7 1934.38  5170.2 1933.59
  5177.1 1934.07  5184.4  1933.5  5232.9 1933.66  5276.2 1933.43  5361.2 1935.57
  5375.3 1934.42  5382.2 1935.35  5389.5 1935.31  5403.2  1939.5  5407.6  1939.5
#Mann= 5 ,-1 , 0
    4518     .05       0  4963.2     .12       0  5003.4     .07       0
  5011.1     .12       0  5232.9     .05       0
Bank Sta=5003.4,5011.1
XS Rating Curve= 0 ,0
Exp/Cntr=0.3,0.1

Type RM Length L Ch R = 1 ,37247   ,399,399,399
BEGIN DESCRIPTION:
Elm 01 91 37246.55
END DESCRIPTION:
XS GIS Cut Line= 3
      1604550.37      6789822.23      1605403.25      6789561.81
      1605974.04      6789401.21
#Sta/Elev= 30
  4106.2 1937.61  4351.5 1937.26    4592 1932.91  4683.3 1929.37  4811.6 1929.21
  4874.3 1931.28  4966.3 1929.16    4989 1928.77  4992.4 1926.51  4992.9 1926.01
  5000.1 1926.51  5028.1 1928.92  5145.8 1927.11  5174.7 1931.71  5179.9  1930.9
  5213.9 1940.96  5219.1 1940.29  5238.7 1947.39  5296.1 1953.85    5353 1957.61
  5373.7 1954.51  5384.1 1954.75  5394.5 1957.42  5399.7 1956.29  5433.7 1966.91
  5438.9 1965.12  5446.5 1968.19    5473  1971.5  5546.3 1975.76  5590.9 1974.38
#Mann= 5 ,-1 , 0
  4106.2     .05       0  4966.3     .12       0  4992.4     .07       0
  5000.1     .12       0  5296.1     .05       0
Bank Sta=4992.4,5000.1
XS Rating Curve= 0 ,0
Exp/Cntr=0.3,0.1

Type RM Length L Ch R = 1 ,36848   ,130,130,130
BEGIN DESCRIPTION:
Elm 01 91 36847.94
END DESCRIPTION:
XS GIS Cut Line= 4
       1604923.6      6789818.61      1605405.42      6789885.89
      1605505.24      6789929.29      1605750.24      6789907.61
#Sta/Elev= 30
  4404.7 1933.68    4439 1932.54  4456.6 1933.07  4476.8  1930.8  4608.1 1926.79
  4688.8 1926.46  4724.9 1925.75  4769.6 1926.26  4860.5 1925.53  4908.1 1926.12
  4923.4 1925.27    4937 1922.64  4945.3 1921.85  4960.4  1919.2  4979.8  1918.8
  4980.3  1918.3  4987.4  1918.3  4987.9  1918.8    5050 1918.88  5059.5 1920.84
  5080.1 1926.41  5099.1 1929.11  5110.2  1931.9  5120.3 1936.93  5130.3 1942.72
  5140.3 1946.25  5150.4 1948.33  5160.4 1949.12  5200.6 1950.19    5246 1949.58
#Mann= 5 ,-1 , 0
  4404.7     .05       0  4979.8     .05       0  4987.9     .05       0
  5059.5     .12       0  5099.1     .05       0
Bank Sta=4979.8,4987.9
XS Rating Curve= 0 ,0
Exp/Cntr=0.3,0.1

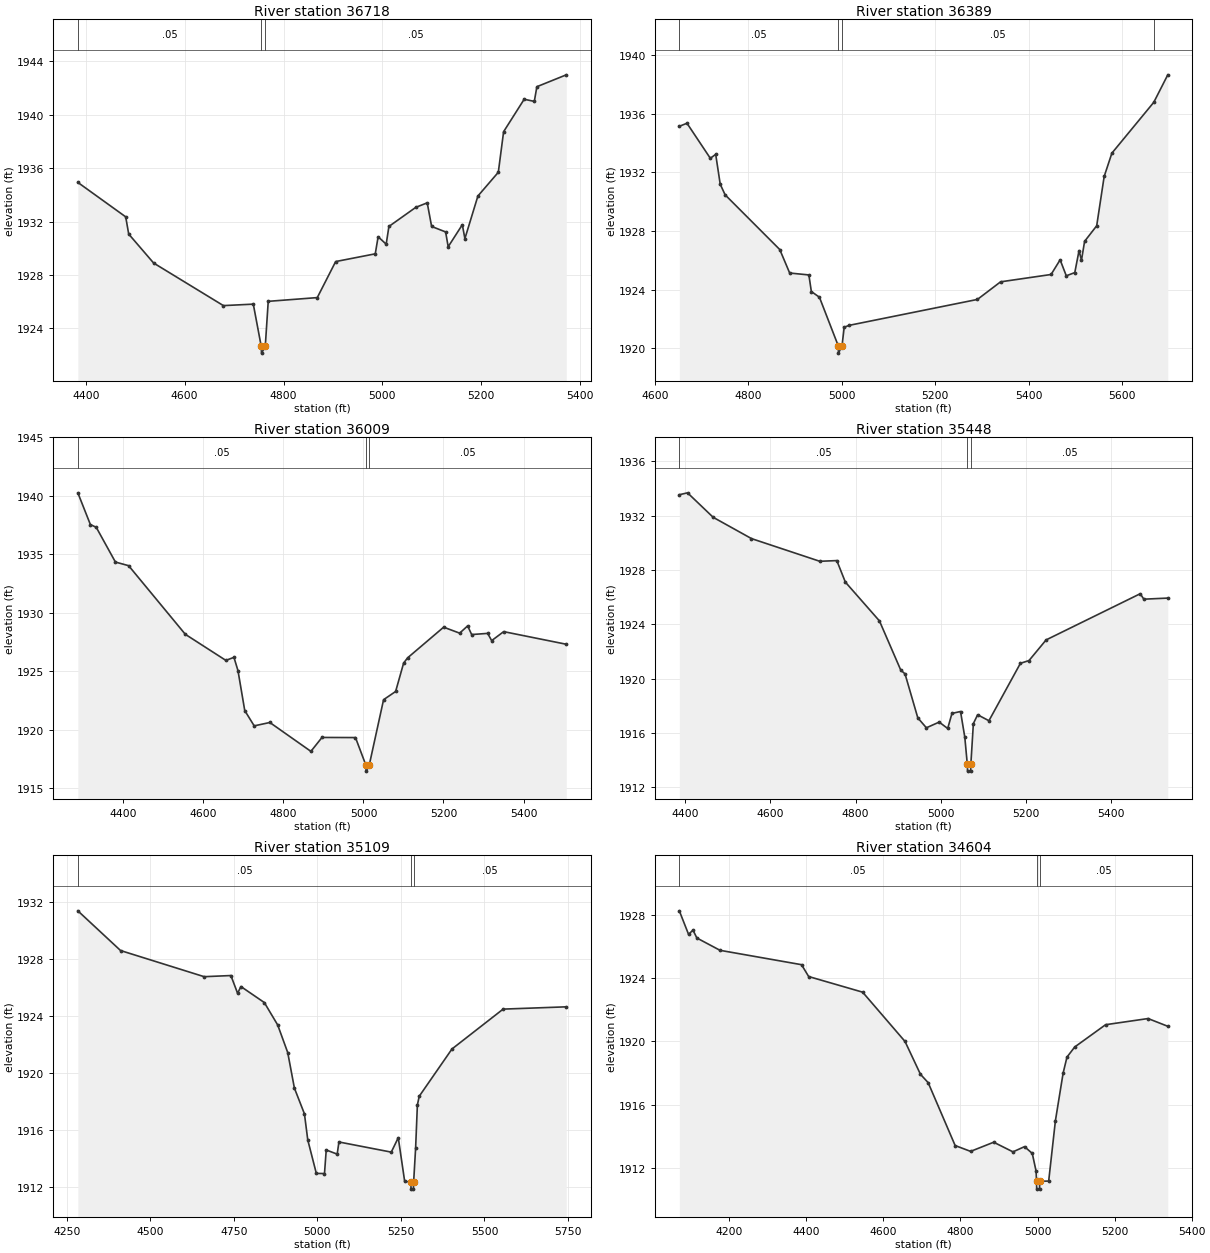
Type RM Length L Ch R = 1 ,36718   ,329,329,329
BEGIN DESCRIPTION:
Elm 01 91 36718.14
END DESCRIPTION:
XS GIS Cut Line= 5
      1604862.87      6789901.08       1605312.1       6789957.5
      1605453.16      6790039.97      1605533.46      6790074.69
      1605806.87      6789996.57
#Sta/Elev= 30
  4383.9 1934.93  4480.7 1932.35  4486.8 1931.06  4537.2 1928.89  4678.3  1925.7
  4738.8 1925.81  4754.9 1922.64  4755.4 1922.14    4763 1922.64    4769 1926.02
  4868.2  1926.3  4905.4    1929  4985.5 1929.58  4991.3 1930.86  5007.6  1930.3
  5013.1 1931.63  5067.4 1933.06  5090.6  1933.4  5099.5 1931.63  5127.8 1931.22
    5133 1930.11  5161.6 1931.76  5166.8 1930.72  5193.1 1933.91  5234.4 1935.69
  5245.1 1938.73  5286.7 1941.16  5307.2    1941  5312.4  1942.1  5371.9 1942.99
#Mann= 3 ,-1 , 0
  4383.9     .05       0  4754.9     .05       0    4763     .05       0
Bank Sta=4754.9,4763
XS Rating Curve= 0 ,0
Exp/Cntr=0.3,0.1

Type RM Length L Ch R = 1 ,36389   ,380,380,380
BEGIN DESCRIPTION:
Elm 01 91 36389.27
END DESCRIPTION:
XS GIS Cut Line= 4
      1604832.47      6790018.25      1605160.19      6790135.45
       1605479.2      6790198.39      1605835.09      6790087.71
#Sta/Elev= 30
  4651.9 1935.14  4668.3 1935.35  4718.3 1932.96  4729.8 1933.23  4739.5 1931.19
    4750 1930.47    4867 1926.74  4888.2 1925.14  4929.3 1925.01  4934.6 1923.88
  4951.9 1923.49  4992.2 1920.18  4992.7 1919.68  5000.3 1920.18  5004.9 1921.44
    5015 1921.57  5290.2 1923.34  5339.8 1924.54  5447.9 1925.04  5467.3 1926.04
  5480.5 1924.95  5498.7 1925.17  5507.8 1926.67    5513 1926.01  5519.7  1927.3
  5545.6 1928.36  5561.6 1931.72  5578.1 1933.31  5667.9 1936.78  5697.8 1938.65
#Mann= 4 ,-1 , 0
  4651.9     .05       0  4992.2     .05       0  5000.3     .05       0
  5667.9     .12       0
Bank Sta=4992.2,5000.3
XS Rating Curve= 0 ,0
Exp/Cntr=0.3,0.1

Type RM Length L Ch R = 1 ,36009   ,561,561,561
BEGIN DESCRIPTION:
Elm 01 91 36008.85
END DESCRIPTION:
XS GIS Cut Line= 3
       1604419.6      6790358.07      1605124.93      6790468.75
       1605631.4      6790481.74
#Sta/Elev= 30
  4286.3 1940.26  4317.6 1937.55  4332.3 1937.31  4380.2 1934.34  4413.2 1934.03
  4554.9 1928.16  4656.2 1925.93  4676.4 1926.19  4686.5 1925.05  4703.4 1921.64
    4727 1920.33  4766.1 1920.62  4868.7 1918.15  4896.4 1919.34  4980.1 1919.33
  5006.2 1916.96  5006.7 1916.46  5014.4 1916.96  5050.3 1922.57  5080.4 1923.27
  5100.4  1925.7  5110.4 1926.15  5200.4 1928.77  5240.4 1928.26  5260.4 1928.88
  5270.4 1928.14  5310.4 1928.24  5320.4 1927.62  5350.4 1928.39  5506.9 1927.31
#Mann= 3 ,-1 , 0
  4286.3     .05       0  5006.2     .05       0  5014.4     .05       0
Bank Sta=5006.2,5014.4
XS Rating Curve= 0 ,0
Exp/Cntr=0.3,0.1

Type RM Length L Ch R = 1 ,35448   ,339,339,339
BEGIN DESCRIPTION:
Elm 01 91 35448.38
END DESCRIPTION:
XS GIS Cut Line= 3
      1604395.72      6790776.91      1605012.08       6790792.1
      1605539.45      6790748.69
#Sta/Elev= 30
  4386.6 1933.54  4405.9 1933.68  4465.9 1931.88  4555.9 1930.31    4716 1928.64
    4756 1928.69    4776 1927.11    4856 1924.25    4906 1920.63    4916 1920.35
    4946 1917.11  4966.1 1916.38  4996.1  1916.8  5016.1 1916.33  5026.1 1917.44
  5046.2 1917.58  5056.2 1915.69  5062.1 1913.69  5062.6 1913.19  5069.9 1913.19
  5070.4 1913.69  5076.3 1916.69  5086.3 1917.34  5112.8  1916.9  5186.7 1921.13
  5206.8 1921.33  5246.9 1922.85  5467.6 1926.25  5476.2 1925.85  5532.3 1925.93
#Mann= 3 ,-1 , 0
  4386.6     .05       0  5062.1     .05       0  5070.4     .05       0
Bank Sta=5062.1,5070.4
XS Rating Curve= 0 ,0
Exp/Cntr=0.3,0.1

Type RM Length L Ch R = 1 ,35109   ,505,505,505
BEGIN DESCRIPTION:
Elm 01 91 35108.69
END DESCRIPTION:
XS GIS Cut Line= 3
      1604337.16      6791052.52      1605051.14       6791061.2
      1605765.69       6790842.5
#Sta/Elev= 30
  4283.5 1931.35  4411.3 1928.57  4661.4 1926.74  4741.4 1926.82  4761.4 1925.58
  4771.4 1926.05  4841.4 1924.93  4881.4 1923.36  4911.4 1921.43  4931.4 1918.94
  4961.4 1917.14  4971.4 1915.31    4997 1912.97  5021.4 1912.96  5026.6 1914.61
  5059.4 1914.32  5064.6 1915.17  5221.2 1914.46  5242.1 1915.47  5261.3 1912.41
  5279.8 1912.37  5280.3 1911.87  5287.6 1911.87  5288.1 1912.37    5294 1914.73
  5299.3 1917.76  5304.8 1918.37  5402.8 1921.68  5555.8 1924.47  5744.8 1924.63
#Mann= 3 ,-1 , 0
  4283.5     .05       0  5279.8     .05       0  5288.1     .05       0
Bank Sta=5279.8,5288.1
XS Rating Curve= 0 ,0
Exp/Cntr=0.3,0.1

Type RM Length L Ch R = 1 ,34604   ,502,502,502
BEGIN DESCRIPTION:
Elm 01 91 34603.91
END DESCRIPTION:
XS GIS Cut Line= 3
      1604469.51      6791223.96      1605400.53      6791191.41
      1605736.04      6791213.05
#Sta/Elev= 30
  4070.2 1928.27  4094.2 1926.78  4105.7 1927.05  4115.7 1926.55  4175.8 1925.77
  4387.4 1924.86  4405.9 1924.11    4546 1923.12    4656    1920  4696.1 1917.92
  4716.1 1917.39  4786.1 1913.41  4826.2 1913.04  4886.2 1913.62  4936.2 1913.01
  4966.2 1913.34  4986.3 1912.91  4996.3 1911.78  4997.3 1911.15  4997.8 1910.65
  5005.2 1910.65  5005.7 1911.15  5028.9 1911.16  5046.4 1914.99  5066.4    1918
  5076.4 1919.01  5096.5 1919.65  5176.6 1921.06  5286.9 1921.45    5338 1920.96
#Mann= 3 ,-1 , 0
  4070.2     .05       0  4997.3     .05       0  5005.7     .05       0
Bank Sta=4997.3,5005.7
XS Rating Curve= 0 ,0
Exp/Cntr=0.3,0.1

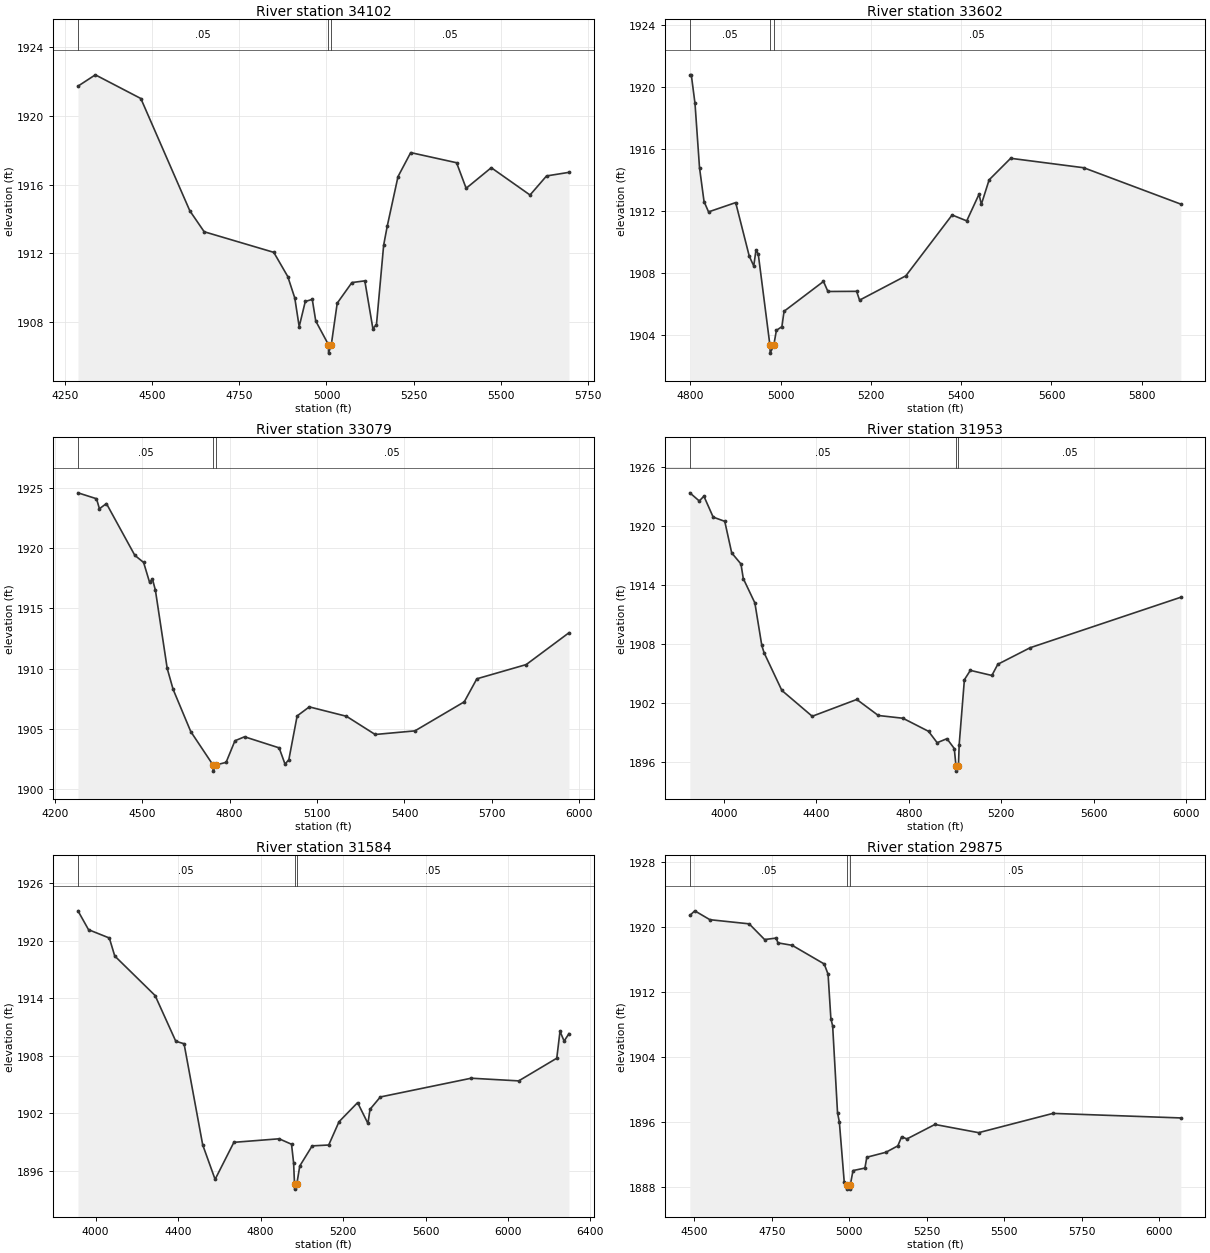
Type RM Length L Ch R = 1 ,34102   ,500,500,500
BEGIN DESCRIPTION:
Elm 01 91 34101.95
END DESCRIPTION:
XS GIS Cut Line= 3
      1604695.29      6791506.86      1605406.18      6791558.94
      1606081.64      6791397.87
#Sta/Elev= 30
  4287.8 1921.73  4337.6 1922.39    4468 1921.01  4608.4 1914.47  4649.5 1913.25
    4849 1912.05  4889.1 1910.64  4909.2 1909.39  4921.8 1907.72  4939.3 1909.19
  4959.3 1909.31  4969.3 1908.05  5005.5 1906.68    5006 1906.18  5013.9 1906.68
  5030.8 1909.09  5072.9 1910.29  5109.9 1910.39    5133 1907.61  5143.3 1907.84
  5163.9 1912.47  5174.2 1913.58    5205 1916.46  5241.4 1917.86  5372.9 1917.27
  5400.3 1915.78  5472.3 1916.98  5583.4 1915.39  5630.7  1916.5    5695 1916.71
#Mann= 3 ,-1 , 0
  4287.8     .05       0  5005.5     .05       0  5013.9     .05       0
Bank Sta=5005.5,5013.9
XS Rating Curve= 0 ,0
Exp/Cntr=0.3,0.1

Type RM Length L Ch R = 1 ,33602   ,523,523,523
BEGIN DESCRIPTION:
Elm 01 91 33602.16
END DESCRIPTION:
XS GIS Cut Line= 3
      1604903.61       6791845.4      1605104.09      6791855.82
      1605950.24      6791590.25
#Sta/Elev= 30
    4799 1920.78  4802.2 1920.78  4810.4 1918.93  4820.4 1914.78  4830.4  1912.6
  4840.4 1911.93  4900.5 1912.53  4930.6 1909.07  4940.5 1908.44  4945.5 1909.47
  4950.6 1909.19  4976.4 1903.31  4976.9 1902.81  4984.8 1903.31  4990.7 1904.28
  5002.9 1904.52  5007.6 1905.51    5095 1907.44  5104.8 1906.79  5168.4  1906.8
  5174.9 1906.23  5277.4  1907.8  5379.9 1911.73  5412.3 1911.35  5439.5 1913.07
  5444.7 1912.42  5461.9    1914  5509.6 1915.39  5671.5 1914.78  5886.6 1912.43
#Mann= 3 ,-1 , 0
    4799     .05       0  4976.4     .05       0  4984.8     .05       0
Bank Sta=4976.4,4984.8
XS Rating Curve= 0 ,0
Exp/Cntr=0.3,0.1

Type RM Length L Ch R = 1 ,33079   ,1126,1126,1126
BEGIN DESCRIPTION:
Elm 01 91 33078.68
END DESCRIPTION:
XS GIS Cut Line= 3
      1604742.11      6792267.27      1605455.66       6792160.5
      1606377.52      6791879.26
#Sta/Elev= 30
  4279.4 1924.59    4343  1924.1  4353.1 1923.27  4377.1  1923.7  4474.4 1919.41
  4504.8 1918.81    4525 1917.18  4535.1 1917.43  4545.2 1916.51  4585.7 1910.02
  4605.9 1908.29  4666.6 1904.78  4743.2    1902  4743.7  1901.5  4751.7    1902
  4787.9 1902.23  4818.2 1904.02  4851.2 1904.35  4969.9 1903.43  4990.1 1902.08
  5003.2 1902.45  5031.7 1906.08  5073.4 1906.83    5201 1906.05  5299.5 1904.54
    5436 1904.84  5605.3 1907.25  5648.5 1909.16  5817.9 1910.34  5964.7 1912.98
#Mann= 3 ,-1 , 0
  4279.4     .05       0  4743.2     .03       0  4751.7     .05       0
Bank Sta=4743.2,4751.7
XS Rating Curve= 0 ,0
Exp/Cntr=0.3,0.1

Type RM Length L Ch R = 1 ,31953   ,369,369,369
BEGIN DESCRIPTION:
Mapping XS b4a205c2
END DESCRIPTION:
XS GIS Cut Line= 4
      1604834.34      6792713.14      1605580.85      6792656.71
      1606600.82      6792300.81      1606851.28      6792141.03
#Sta/Elev= 30
  3852.1 1923.36  3892.9 1922.53  3912.9 1923.02    3953 1920.89  4003.2 1920.46
  4033.3 1917.25  4073.4 1916.12  4083.4 1914.64  4133.6 1912.16  4163.6 1907.83
  4173.7 1907.08  4250.4 1903.26  4381.9 1900.63  4574.8 1902.34  4668.1 1900.71
  4774.6 1900.43  4885.5  1899.1  4922.9 1897.94  4965.2 1898.35    4997 1897.35
  5004.5 1895.55    5005 1895.05    5015 1895.55  5018.2 1897.74  5040.8 1904.35
  5066.6  1905.3  5159.8 1904.78  5185.5 1905.92  5325.3  1907.6  5978.1 1912.74
#Mann= 3 ,-1 , 0
  3852.1     .05       0  5004.5     .05       0    5015     .05       0
Bank Sta=5004.5,5015
XS Rating Curve= 0 ,0
Exp/Cntr=0.3,0.1

Type RM Length L Ch R = 1 ,31584   ,1709,1709,1709
BEGIN DESCRIPTION:
Mapping XS 77559c60
END DESCRIPTION:
XS GIS Cut Line= 4
       1604834.3        6792839.      1605220.61      6792891.09
      1605546.13      6792865.05      1607208.42      6792769.56
#Sta/Elev= 30
  3914.2 1923.14  3965.4 1921.17  4066.3  1920.3  4092.6 1918.42  4288.3 1914.29
  4388.7 1909.51  4428.8 1909.25  4519.1 1898.69  4579.3 1895.08  4670.4 1898.95
  4889.9 1899.32    4950 1898.75    4960 1896.82  4964.6 1894.56  4965.1 1894.06
  4975.3 1894.56    4990 1896.48  5050.1 1898.58  5130.3 1898.67  5180.3  1901.1
  5270.5  1903.1  5320.6 1900.92  5330.6  1902.4  5380.7 1903.69  5821.4 1905.65
  6051.8 1905.37  6236.4 1907.74  6252.1 1910.55  6272.1 1909.53  6295.6 1910.31
#Mann= 3 ,-1 , 0
  3914.2     .05       0  4964.6     .05       0  4975.3     .05       0
Bank Sta=4964.6,4975.3
XS Rating Curve= 0 ,0
Exp/Cntr=0.3,0.1

Type RM Length L Ch R = 1 ,29875   ,424,424,424
BEGIN DESCRIPTION:
Elm 01 91 29875.16
END DESCRIPTION:
XS GIS Cut Line= 3
      1604759.65      6792913.17      1605204.48      6793171.39
      1606165.89      6793637.98
#Sta/Elev= 30
    4486 1921.42  4501.8 1921.99  4550.6  1920.9  4677.2 1920.39    4727 1918.46
  4764.2 1918.64    4770 1918.05  4815.9 1917.75  4919.1 1915.46  4931.6  1914.2
  4940.6 1908.75  4946.4 1907.83  4962.1 1897.15  4967.9 1896.06  4983.6  1888.7
  4992.3 1888.28  4992.8 1887.78  5002.7 1887.78  5003.2 1888.28    5012 1890.06
  5050.4 1890.37  5056.5  1891.7  5118.1 1892.31  5156.5  1893.1  5168.8 1894.22
  5185.8 1893.95  5276.1 1895.73    5417 1894.72  5656.7 1897.09    6069 1896.53
#Mann= 3 ,-1 , 0
    4486     .05       0  4992.3     .05       0  5003.2     .05       0
Bank Sta=4992.3,5003.2
XS Rating Curve= 0 ,0
Exp/Cntr=0.3,0.1

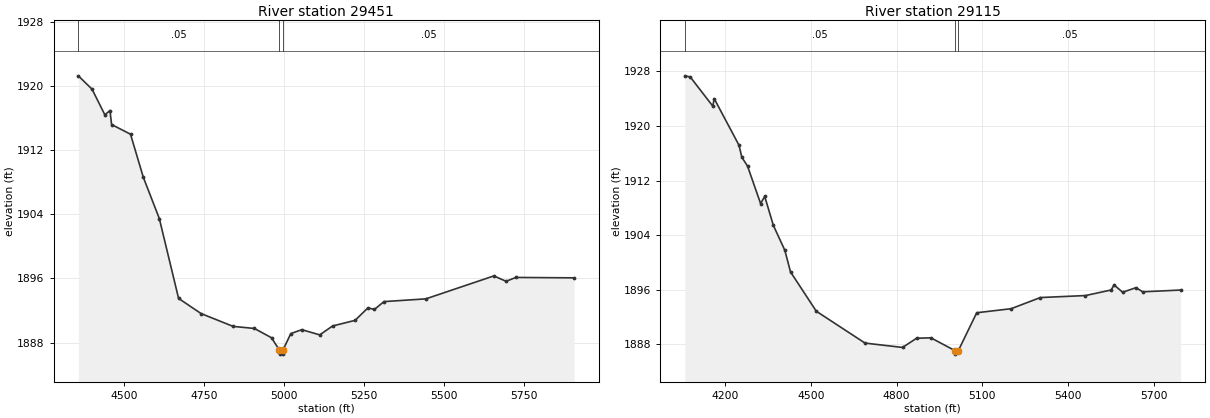
Type RM Length L Ch R = 1 ,29451   ,336,336,336
BEGIN DESCRIPTION:
Elm 01 91 29450.78
END DESCRIPTION:
XS GIS Cut Line= 3
      1604462.31      6793577.42      1605108.13      6793548.78
       1606006.6       6793624.3
#Sta/Elev= 30
  4357.2 1921.27  4399.9 1919.61    4440 1916.41    4456 1916.94    4461  1915.2
  4520.1 1913.99  4560.1 1908.62  4610.1 1903.47  4670.2 1893.52  4740.3 1891.63
  4840.4 1890.03  4906.9 1889.77  4960.5 1888.61    4985 1887.07  4985.5 1886.57
  4995.5 1886.57    4996 1887.07  5020.6 1889.13  5054.9 1889.62  5110.9 1888.97
    5151 1890.08  5221.3 1890.78  5261.4 1892.34  5281.5 1892.14  5311.6 1893.12
  5442.1 1893.46  5654.4 1896.32  5692.9 1895.65  5723.1 1896.13  5905.3 1896.08
#Mann= 3 ,-1 , 0
  4357.2     .05       0    4985     .05       0    4996     .05       0
Bank Sta=4985,4996
XS Rating Curve= 0 ,0
Exp/Cntr=0.3,0.1

Type RM Length L Ch R = 1 ,29115   ,185,185,185
BEGIN DESCRIPTION:
Elm 01 91 29115.08
END DESCRIPTION:
XS GIS Cut Line= 3
      1604365.98      6793809.19      1605303.44       6793751.9
      1606097.69      6793728.47
#Sta/Elev= 30
  4059.7 1927.36  4078.8 1927.19  4157.5 1922.92  4162.6 1924.01  4249.1 1917.19
  4259.1 1915.42  4279.1 1914.12  4324.7 1908.63  4339.2 1909.67  4369.3 1905.43
  4409.4 1901.78  4429.4  1898.6  4519.6 1892.83  4689.9 1888.16  4821.1 1887.52
  4870.2 1888.87  4920.3 1888.93    5005 1887.04  5005.5 1886.54    5016 1887.04
  5080.5 1892.61  5200.6  1893.2  5303.2 1894.84  5460.7 1895.13  5550.7 1895.95
  5560.7 1896.69  5590.7 1895.62  5637.7 1896.29  5660.8 1895.68  5793.5 1895.94
#Mann= 3 ,-1 , 0
  4059.7     .05       0    5005     .03       0    5016     .05       0
Bank Sta=5005,5016
XS Rating Curve= 0 ,0
Exp/Cntr=0.3,0.1