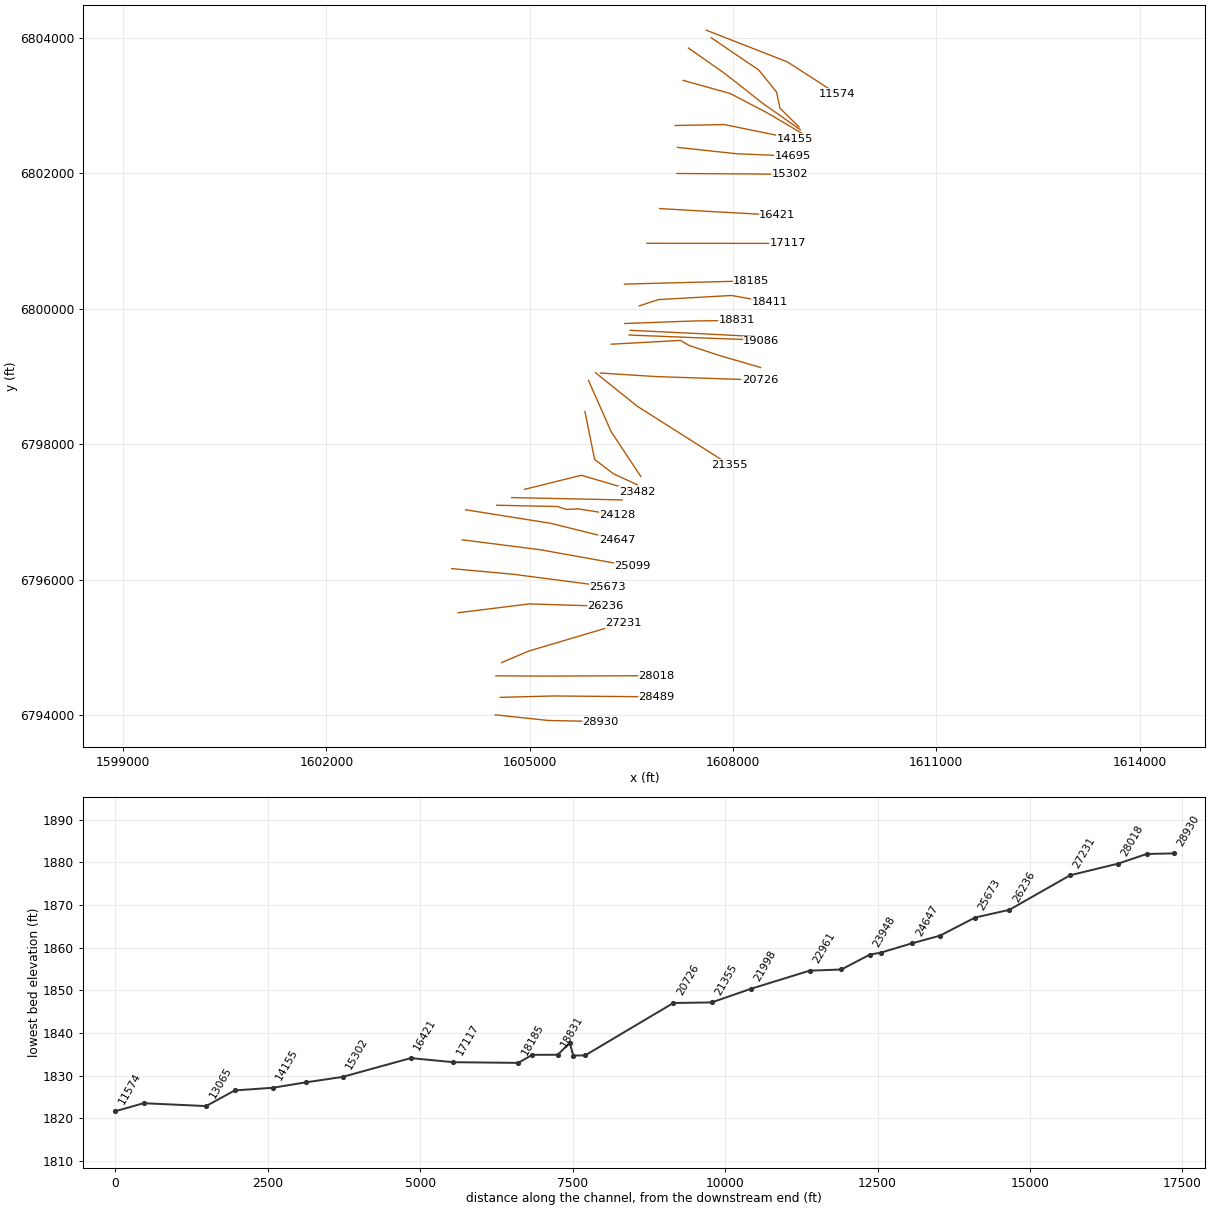
HEC-RAS study Elm 01 91.prj: Elm 01 91 Base Level Engineering

--- Elm 01 91.g01 (geometry) --- (continued)

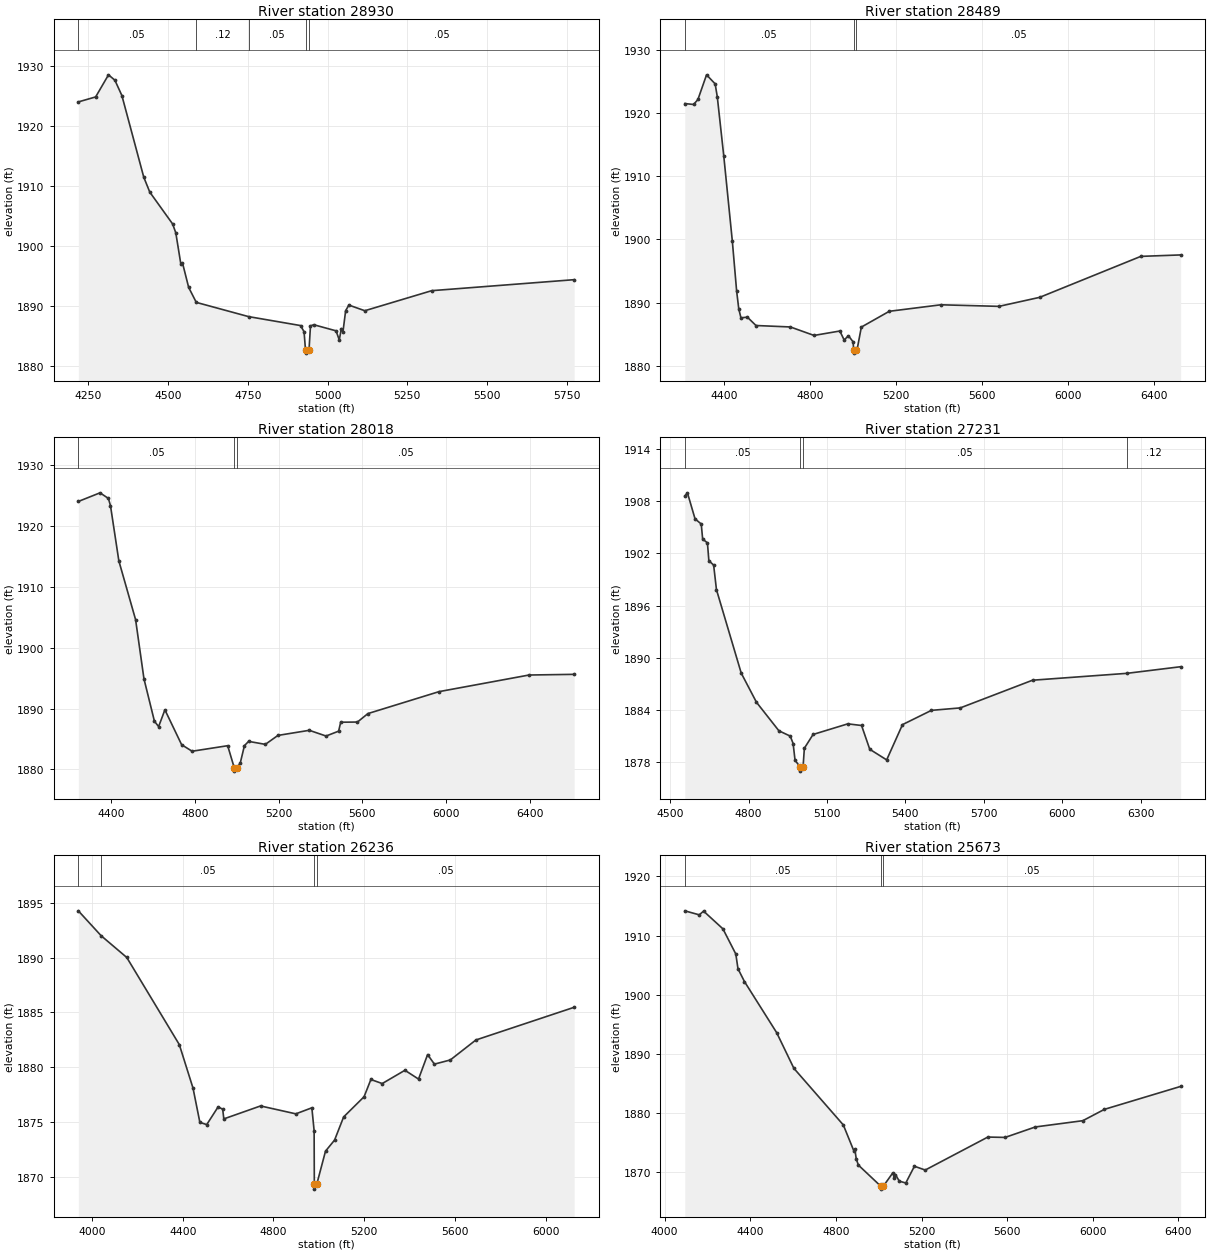
Type RM Length L Ch R = 1 ,28930   ,441,441,441
BEGIN DESCRIPTION:
Elm 01 91 28929.57
END DESCRIPTION:
XS GIS Cut Line= 3
      1604490.98      6794007.11       1605274.8      6793923.78
       1606041.5      6793908.18
#Sta/Elev= 30
  4218.3 1923.96  4272.6 1924.79  4312.9 1928.47    4333 1927.57  4354.9 1925.02
  4423.5 1911.43  4442.4 1908.94    4514 1903.64    4524 1902.16    4540  1896.9
    4545 1897.15  4564.3 1893.08  4588.2 1890.58  4752.3 1888.21  4915.2 1886.72
  4926.3 1885.69  4930.8 1882.63  4931.3 1882.13  4941.8 1882.63  4946.4 1886.66
  4956.5 1886.86  5026.7 1885.84  5036.7 1884.32  5043.2 1886.22  5048.2 1885.64
  5056.7  1889.2  5066.8 1890.13  5116.8 1889.19  5326.8 1892.53  5773.4 1894.36
#Mann= 5 ,-1 , 0
  4218.3     .05       0  4588.2     .12       0  4752.3     .05       0
  4930.8     .05       0  4941.8     .05       0
Bank Sta=4930.8,4941.8
XS Rating Curve= 0 ,0
Exp/Cntr=0.3,0.1

Type RM Length L Ch R = 1 ,28489   ,471,471,471
BEGIN DESCRIPTION:
Elm 01 91 28488.88
END DESCRIPTION:
XS GIS Cut Line= 3
      1604563.87      6794264.92       1605346.7      6794285.66
      1606870.44      6794272.74
#Sta/Elev= 30
  4216.9 1921.49    4258 1921.35    4278 1922.14  4318.1 1926.04  4358.1 1924.61
  4368.1 1922.56  4398.1 1913.23  4438.1 1899.71  4458.1 1891.81  4468.1 1888.98
  4478.1 1887.59  4508.1 1887.69  4548.1 1886.37  4708.2 1886.14  4818.2  1884.8
  4938.3  1885.5  4958.3 1884.08  4978.3 1884.75    5000 1883.78  5002.7  1882.5
  5003.2    1882  5013.9  1882.5  5018.3 1882.52  5038.3 1886.12  5168.3 1888.62
  5408.3 1889.65  5678.3  1889.4  5868.3 1890.83  6338.4 1897.31  6523.8 1897.54
#Mann= 3 ,-1 , 0
  4216.9     .05       0  5002.7     .05       0  5013.9     .05       0
Bank Sta=5002.7,5013.9
XS Rating Curve= 0 ,0
Exp/Cntr=0.3,0.1

Type RM Length L Ch R = 1 ,28018   ,787,787,787
BEGIN DESCRIPTION:
Elm 01 91 28018.96
END DESCRIPTION:
XS GIS Cut Line= 3
       1604501.4      6794582.63      1605254.83      6794579.16
      1606870.38      6794585.23
#Sta/Elev= 30
    4243 1924.06  4346.6 1925.48  4386.6 1924.56  4396.6 1923.37  4436.6 1914.29
  4516.6 1904.63  4556.6  1894.9  4606.6 1887.93  4626.6 1887.05  4656.6 1889.81
  4736.6 1884.07  4786.6    1883  4956.6 1883.91  4988.4 1880.23  4988.9 1879.73
  4999.7 1880.23  5016.6 1881.05  5036.6 1883.92  5056.6 1884.62  5136.6 1884.13
  5196.6  1885.6  5346.6 1886.44  5426.6  1885.5  5486.6  1886.3  5496.6 1887.77
  5576.6  1887.8  5626.6 1889.19  5966.6  1892.8  6396.6 1895.53    6612 1895.64
#Mann= 3 ,-1 , 0
    4243     .05       0  4988.4     .05       0  4999.7     .05       0
Bank Sta=4988.4,4999.7
XS Rating Curve= 0 ,0
Exp/Cntr=0.3,0.1

Type RM Length L Ch R = 1 ,27231   ,995,995,995
BEGIN DESCRIPTION:
Elm 01 91 27231.12
END DESCRIPTION:
XS GIS Cut Line= 3
      1604583.44      6794777.93      1604989.73      6794949.82
      1606384.92      6795363.56
#Sta/Elev= 30
  4556.3  1908.6  4566.4 1908.96  4595.5 1905.97  4619.2 1905.38  4624.6 1903.65
  4642.9 1903.21  4648.3 1901.17  4666.6 1900.66  4677.4 1897.84  4772.2 1888.25
  4830.4 1884.91  4916.3 1881.63  4959.7 1881.02  4970.6 1880.17    4978 1878.24
  4997.3  1877.5  4997.8    1877  5008.7  1877.5  5013.6 1879.63  5046.9 1881.21
  5179.8 1882.43  5232.4 1882.24  5263.7 1879.51  5328.4 1878.29  5388.9 1882.34
  5499.7 1883.98  5609.9 1884.26  5886.2 1887.44  6247.2 1888.23  6452.7 1888.99
#Mann= 4 ,-1 , 0
  4556.3     .05       0  4997.3     .05       0  5008.7     .05       0
  6247.2     .12       0
Bank Sta=4997.3,5008.7
XS Rating Curve= 0 ,0
Exp/Cntr=0.3,0.1

Type RM Length L Ch R = 1 ,26236   ,563,563,563
BEGIN DESCRIPTION:
Elm 01 91 26235.65
END DESCRIPTION:
XS GIS Cut Line= 3
      1603943.05      6795514.09      1604993.42       6795644.3
      1606120.98       6795609.6
#Sta/Elev= 30
  3939.7 1894.26  4040.3 1891.99  4153.3 1890.01    4385 1882.07  4445.5  1878.1
  4475.7 1874.98  4505.9 1874.78  4556.3  1876.4  4576.3 1876.18  4581.3  1875.3
  4743.2 1876.48  4898.9 1875.76  4969.5 1876.31  4979.5 1874.22  4980.4  1869.4
  4980.9  1868.9  4991.8  1869.4  5029.7 1872.36  5069.7 1873.37  5109.7 1875.48
  5199.8 1877.32  5229.8 1878.89  5279.8 1878.52  5379.9 1879.73  5439.9 1878.93
  5479.9 1881.16  5509.9 1880.29    5580 1880.67  5692.8 1882.49  6126.2 1885.47
#Mann= 4 ,-1 , 0
  3939.7     .12       0  4040.3     .05       0  4980.4     .05       0
  4991.8     .05       0
Bank Sta=4980.4,4991.8
XS Rating Curve= 0 ,0
Exp/Cntr=0.3,0.1

Type RM Length L Ch R = 1 ,25673   ,574,574,574
BEGIN DESCRIPTION:
Elm 01 91 25672.7
END DESCRIPTION:
XS GIS Cut Line= 3
      1603847.62      6796165.13      1604750.36      6796082.67
      1606147.93      6795900.38
#Sta/Elev= 30
  4094.2 1914.18  4161.9  1913.5  4181.9 1914.13  4272.3 1911.13  4332.5 1906.87
  4342.6 1904.38  4372.7 1902.22  4523.4 1893.56  4603.7 1887.53  4834.6 1877.95
  4883.5 1873.59  4888.5 1873.86  4894.9 1872.22  4904.9 1871.16  5009.5 1867.59
    5010 1867.09  5021.5 1867.59  5065.9 1869.85  5073.2  1868.9  5078.2 1869.55
  5096.1 1868.44  5126.4 1868.13  5166.7 1870.96  5217.2 1870.32  5509.6  1875.9
  5590.3 1875.84  5731.5 1877.61  5953.3 1878.67  6054.2 1880.59  6410.1 1884.47
#Mann= 3 ,-1 , 0
  4094.2     .05       0  5009.5     .05       0  5021.5     .05       0
Bank Sta=5009.5,5021.5
XS Rating Curve= 0 ,0
Exp/Cntr=0.3,0.1

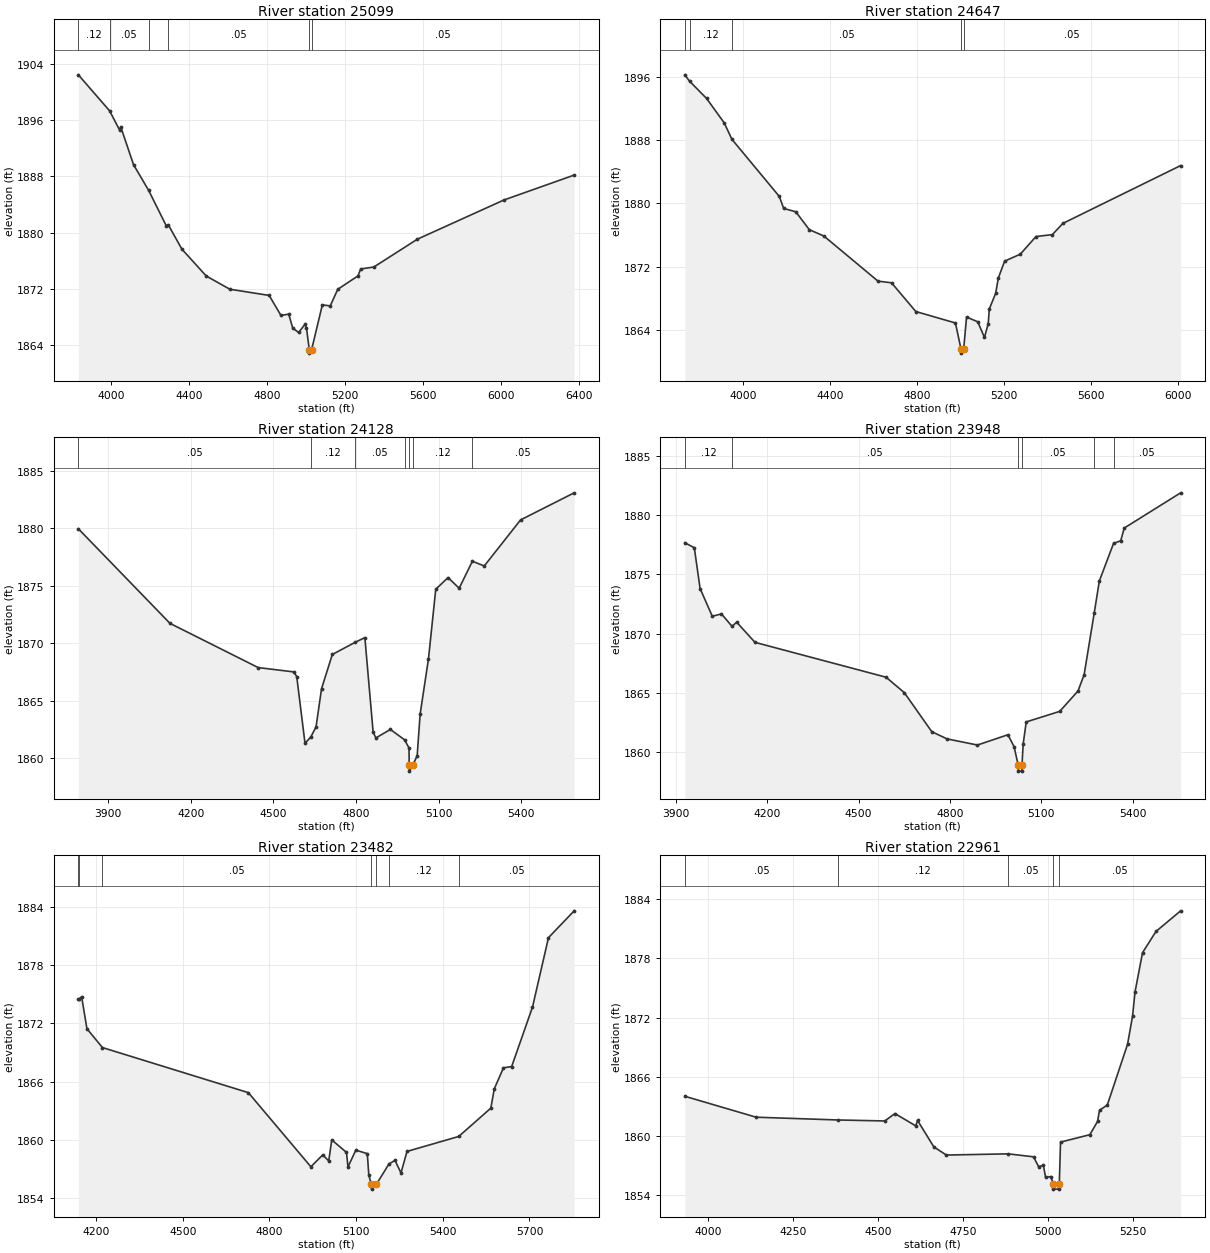
Type RM Length L Ch R = 1 ,25099   ,452,452,452
BEGIN DESCRIPTION:
Elm 01 91 25099.02
END DESCRIPTION:
XS GIS Cut Line= 3
      1604003.87      6796590.47      1605158.35      6796442.91
      1606516.81      6796199.86
#Sta/Elev= 30
  3831.6 1902.48  3992.1 1897.35  4043.9 1894.58  4048.9 1895.09    4115 1889.67
  4192.4 1886.02  4283.1 1880.96  4292.6 1881.14  4362.9 1877.65    4488 1873.82
    4609 1871.94  4810.6 1871.06  4871.1 1868.21  4911.1 1868.39  4931.6 1866.41
  4961.9 1865.78  4995.1 1866.96  5002.2 1866.39  5016.5 1863.34    5017 1862.84
  5028.5 1863.34  5083.5 1869.71  5124.1 1869.57  5162.5 1871.93  5266.4 1873.84
  5280.2 1874.83  5347.6  1875.1  5571.1 1879.07    6015 1884.65  6375.5  1888.2
#Mann= 6 ,-1 , 0
  3831.6     .12       0  3992.1     .05       0  4192.4     .12       0
  4292.6     .05       0  5016.5     .05       0  5028.5     .05       0
Bank Sta=5016.5,5028.5
XS Rating Curve= 0 ,0
Exp/Cntr=0.3,0.1

Type RM Length L Ch R = 1 ,24647   ,519,519,519
BEGIN DESCRIPTION:
Elm 01 91 24647.25
END DESCRIPTION:
XS GIS Cut Line= 3
       1604055.9      6797033.19      1605310.26      6796833.54
      1606290.57      6796590.63
#Sta/Elev= 30
  3731.7 1896.26  3753.4 1895.46    3832 1893.27  3913.1 1890.18  3948.3 1888.11
  4166.2 1880.89  4186.4 1879.37    4242 1878.95  4304.2 1876.69  4371.4 1875.88
  4620.2 1870.18  4682.4 1869.97    4794 1866.34  4976.3 1864.89  5001.9 1861.58
  5002.4 1861.08  5014.1 1861.58  5027.3 1865.64  5078.8 1865.04  5109.8 1863.06
    5127  1864.8  5132.2 1866.67  5161.3 1868.65  5173.5 1870.57  5202.5 1872.71
  5274.6 1873.59  5346.7 1875.82  5421.9 1876.06  5470.3 1877.48  6011.8 1884.79
#Mann= 5 ,-1 , 0
  3731.7     .05       0  3753.4     .12       0  3948.3     .05       0
  5001.9     .05       0  5014.1     .05       0
Bank Sta=5001.9,5014.1
XS Rating Curve= 0 ,0
Exp/Cntr=0.3,0.1

Type RM Length L Ch R = 1 ,24128   ,180,180,180
BEGIN DESCRIPTION:
Elm 01 91 24128.18
END DESCRIPTION:
XS GIS Cut Line= 5
      1604512.47      6797100.72      1605410.08      6797081.63
      1605538.56      6797038.22       1605713.9       6797046.9
      1606297.21      6796954.89
#Sta/Elev= 30
  3791.9 1879.97  4124.5 1871.73  4444.6 1867.88  4574.6  1867.5  4584.6 1867.08
  4614.6 1861.28    4636 1861.85  4654.6 1862.71  4674.6 1866.04  4713.7 1869.02
  4795.8 1870.07  4831.8 1870.49  4861.8 1862.26  4871.8 1861.75  4924.4 1862.49
  4976.4 1861.58    4992 1860.87  4992.8 1859.36  4993.3 1858.86  5005.1 1859.36
  5021.6 1860.19  5032.4 1863.82  5062.7 1868.64  5089.1  1874.7  5133.6 1875.72
  5174.1 1874.79    5222 1877.14  5265.2 1876.73  5396.8 1880.74  5591.4  1883.1
#Mann= 7 ,-1 , 0
  3791.9     .05       0    4636     .12       0  4795.8     .05       0
  4976.4     .12       0  4992.8     .07       0  5005.1     .12       0
    5222     .05       0
Bank Sta=4992.8,5005.1
XS Rating Curve= 0 ,0
Exp/Cntr=0.3,0.1

Type RM Length L Ch R = 1 ,23948   ,466,466,466
BEGIN DESCRIPTION:
Elm 01 91 23947.9
END DESCRIPTION:
XS GIS Cut Line= 3
      1604734.77      6797213.57      1605807.65        6797191.
       1606361.6      6797178.88
#Sta/Elev= 30
  3929.6 1877.66  3960.8 1877.24  3979.8  1873.8  4019.8 1871.46  4049.9 1871.66
  4084.5 1870.61  4099.9 1870.96  4159.9 1869.26    4590 1866.32    4650 1865.02
    4740 1861.73    4790 1861.12    4890  1860.6  4990.1 1861.47  5010.1 1860.47
  5023.9  1858.9  5024.4  1858.4  5035.7  1858.4  5036.2  1858.9  5040.1 1860.69
  5050.1 1862.55  5160.1 1863.44  5220.1 1865.16  5240.1 1866.53  5273.1 1871.71
  5290.1 1874.44  5336.6  1877.6  5360.2 1877.83  5371.8  1878.9  5556.8 1881.87
#Mann= 6 ,-1 , 0
  3929.6     .12       0  4084.5     .05       0  5023.9     .05       0
  5036.2     .05       0  5273.1     .12       0  5336.6     .05       0
Bank Sta=5023.9,5036.2
XS Rating Curve= 0 ,0
Exp/Cntr=0.3,0.1

Type RM Length L Ch R = 1 ,23482   ,521,521,521
BEGIN DESCRIPTION:
Elm 01 91 23797.67
END DESCRIPTION:
XS GIS Cut Line= 3
      1604923.95      6797335.09      1605760.03      6797542.84
      1606580.31       6797303.1
#Sta/Elev= 30
  4138.5 1874.49  4140.7 1874.49  4149.9 1874.75  4168.3 1871.45  4221.9 1869.51
  4726.9 1864.86  4943.3 1857.22  4984.5 1858.44  5005.2 1857.82  5015.6 1859.99
  5066.6  1858.7  5071.8  1857.2  5098.9 1858.93  5138.7 1858.57  5143.9 1856.34
  5152.7 1855.41  5153.2 1854.91  5170.3 1855.41  5213.4  1857.5  5234.4 1857.88
  5255.2 1856.58  5276.1  1858.8    5455 1860.34  5566.2 1863.26  5578.2 1865.26
    5610 1867.42  5638.3 1867.55  5710.4 1873.68  5765.7 1880.84  5854.6 1883.61
#Mann= 7 ,-1 , 0
  4138.5     .05       0  4140.7     .12       0  4221.9     .05       0
  5152.7     .03       0  5170.3     .05       0  5213.4     .12       0
    5455     .05       0
Bank Sta=5152.7,5170.3
XS Rating Curve= 0 ,0
Exp/Cntr=0.3,0.1

Type RM Length L Ch R = 1 ,22961   ,963,963,963
BEGIN DESCRIPTION:
Elm 01 91 22961.21
END DESCRIPTION:
XS GIS Cut Line= 4
      1605814.27      6798483.51       1605957.5      6797776.01
      1606230.94      6797567.68       1606586.6      6797402.87
#Sta/Elev= 30
  3932.1 1864.03  4141.8 1861.91  4382.5 1861.63  4519.9 1861.53  4549.9 1862.28
  4611.1 1861.03  4616.2 1861.59  4664.3  1858.9  4701.1 1858.08  4883.3  1858.2
  4957.4  1857.9  4971.9 1856.92  4986.4 1857.03  4992.7 1855.81  5008.3  1855.9
  5015.4 1855.13  5015.9 1854.63  5032.5 1854.63    5033 1855.13  5036.7 1859.39
  5122.8 1860.14  5145.5 1861.48  5151.3 1862.61  5174.2 1863.15  5233.6 1869.28
  5248.4 1872.14  5255.7  1874.6  5277.7 1878.56  5317.2 1880.71  5389.7  1882.8
#Mann= 5 ,-1 , 0
  3932.1     .05       0  4382.5     .12       0  4883.3     .05       0
  5015.4     .05       0    5033     .05       0
Bank Sta=5015.4,5033
XS Rating Curve= 0 ,0
Exp/Cntr=0.3,0.1

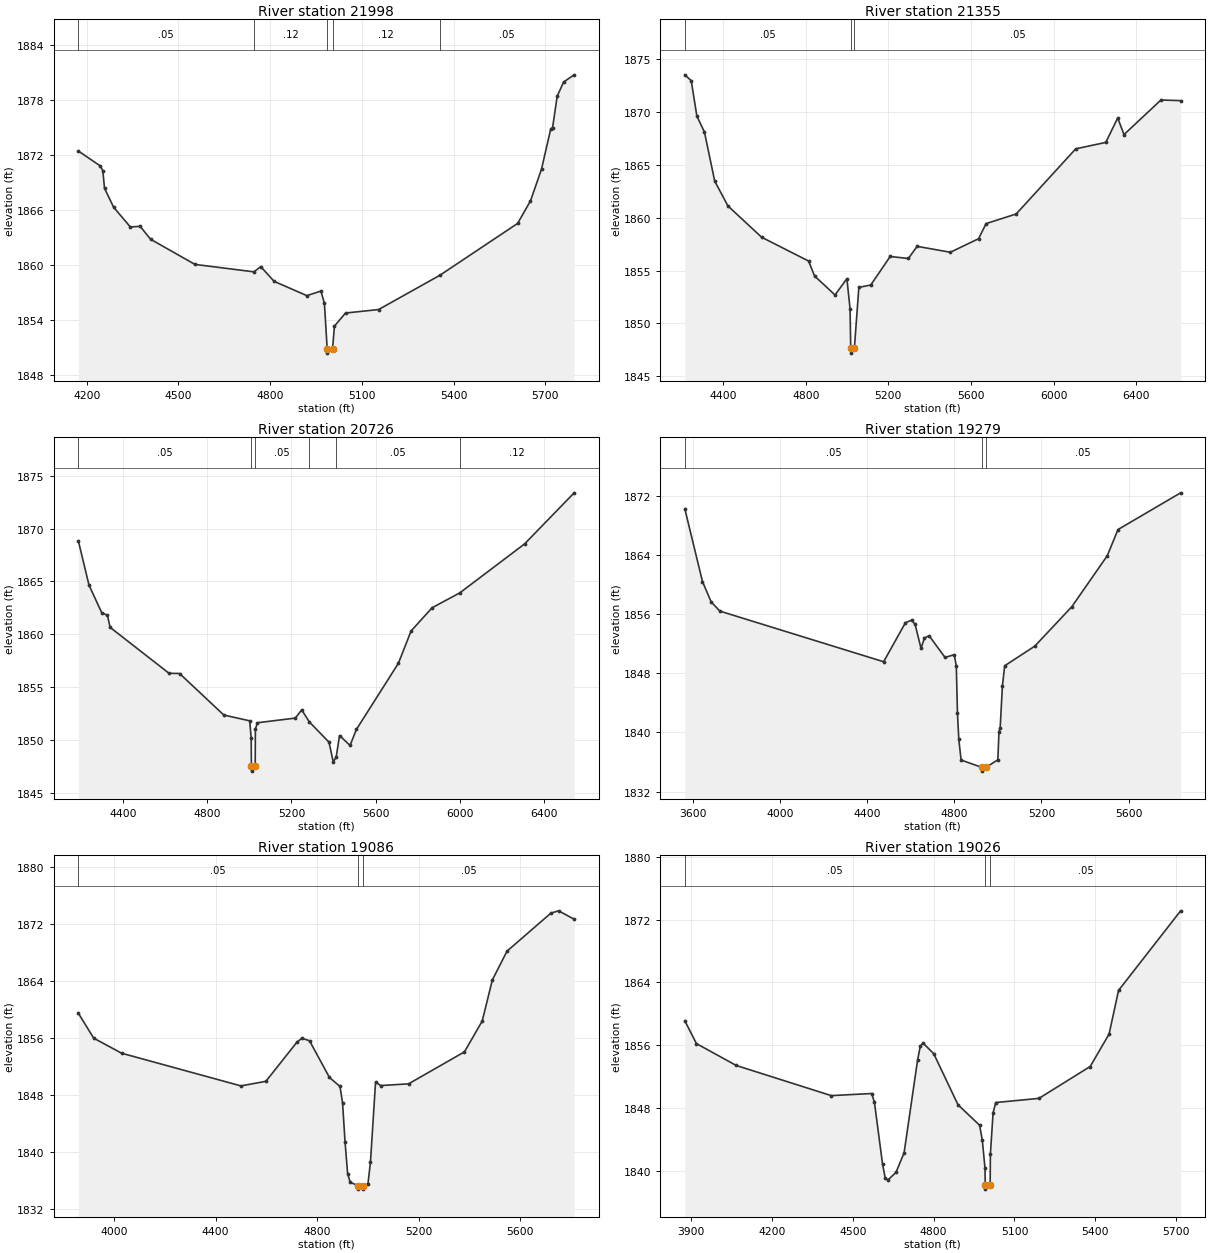
Type RM Length L Ch R = 1 ,21998   ,643,643,643
BEGIN DESCRIPTION:
Elm 01 91 21997.54
END DESCRIPTION:
XS GIS Cut Line= 3
      1605866.35      6798943.56      1606200.56      6798188.34
      1606638.95      6797524.25
#Sta/Elev= 30
  4172.8 1872.46  4244.5 1870.83    4253 1870.31  4258.4 1868.39  4288.2 1866.32
  4342.9 1864.16  4374.9 1864.23  4409.1 1862.82  4554.3 1860.07  4747.1 1859.26
  4769.4 1859.83  4813.1 1858.22  4920.1 1856.66  4966.2 1857.16  4977.6 1855.83
  4986.6 1850.88  4987.1 1850.38  5004.3 1850.88  5010.4 1853.33  5046.6 1854.76
  5154.8 1855.14    5355 1858.88  5609.5 1864.55  5651.6 1867.01  5687.7 1870.49
  5717.9 1874.88  5723.9 1875.02  5738.9 1878.44    5760    1880  5794.4 1880.78
#Mann= 5 ,-1 , 0
  4172.8     .05       0  4747.1     .12       0  4986.6     .07       0
  5004.3     .12       0    5355     .05       0
Bank Sta=4986.6,5004.3
XS Rating Curve= 0 ,0
Exp/Cntr=0.3,0.1

Type RM Length L Ch R = 1 ,21355   ,629,629,629
BEGIN DESCRIPTION:
Elm 01 91 21354.76
END DESCRIPTION:
XS GIS Cut Line= 3
      1605970.55      6799056.37      1606586.85       6798561.6
      1607946.28      6797699.26
#Sta/Elev= 30
  4214.6 1873.51  4245.7 1872.96    4273 1869.61  4309.7  1868.1  4359.4 1863.46
  4423.4 1861.11  4586.6 1858.15  4813.8  1855.9  4842.6 1854.49  4941.8 1852.69
  4999.4 1854.23  5014.6 1851.37  5017.8 1847.69  5018.3 1847.19  5035.6 1847.69
  5057.2 1853.41  5114.8 1853.63  5208.8 1856.33  5296.9 1856.14  5339.3 1857.29
  5500.1 1856.73  5636.7 1858.01  5673.1 1859.44  5818.8 1860.35  6106.9 1866.51
  6252.6 1867.12  6310.2 1869.43  6340.7 1867.86  6519.5 1871.13  6614.8 1871.07
#Mann= 3 ,-1 , 0
  4214.6     .05       0  5017.8     .05       0  5035.6     .05       0
Bank Sta=5017.8,5035.6
XS Rating Curve= 0 ,0
Exp/Cntr=0.3,0.1

Type RM Length L Ch R = 1 ,20726   ,1447,1447,1447
BEGIN DESCRIPTION:
Elm 01 91 20725.67
END DESCRIPTION:
XS GIS Cut Line= 3
      1606044.35      6799052.05      1606855.94      6798999.97
      1608400.51      6798947.91
#Sta/Elev= 30
    4186 1868.85  4236.8 1864.65  4296.9 1862.06  4324.6 1861.79    4337 1860.66
  4617.5 1856.31  4667.6 1856.29  4878.1 1852.36  5001.3 1851.81  5008.3 1850.16
  5009.3 1847.55  5009.8 1847.05  5027.4 1847.55  5028.3 1851.04  5038.3 1851.63
  5218.4 1852.07  5248.5 1852.85  5285.2  1851.7  5378.5 1849.79  5398.5 1847.92
  5412.6 1848.38  5428.6 1850.42  5478.6 1849.48  5508.6 1850.99  5708.7 1857.26
  5768.8 1860.31  5868.8 1862.51  6001.3 1863.93  6309.1 1868.56  6544.7 1873.39
#Mann= 6 ,-1 , 0
    4186     .05       0  5009.3     .05       0  5027.4     .05       0
  5285.2     .12       0  5412.6     .05       0  6001.3     .12       0
Bank Sta=5009.3,5027.4
XS Rating Curve= 0 ,0
Exp/Cntr=0.3,0.1

Type RM Length L Ch R = 1 ,19279   ,193,193,193
BEGIN DESCRIPTION:
Mapping XS d450de37
END DESCRIPTION:
XS GIS Cut Line= 5
      1606204.06      6799477.42      1607224.88      6799532.98
      1607353.85      6799457.49      1607804.37      6799309.06
      1608408.09      6799133.28
#Sta/Elev= 30
  3563.6 1870.27  3644.7 1860.41  3684.7 1857.65  3724.8 1856.41  4475.9 1849.56
    4576 1854.85  4604.6 1855.19  4620.3 1854.61  4647.5 1851.37  4663.2 1852.79
  4684.7 1853.08  4757.6 1850.14  4799.8 1850.52  4809.3 1848.99  4814.6 1842.61
  4820.8 1839.05  4831.3 1836.26  4927.3 1835.26  4927.8 1834.76  4945.5 1835.26
  4999.8 1836.29  5005.2 1840.12  5010.5 1840.59  5020.9 1846.32  5031.4 1849.02
  5169.3 1851.67  5339.6 1857.02    5502 1863.91  5551.1 1867.45  5838.5 1872.42
#Mann= 3 ,-1 , 0
  3563.6     .05       0  4927.3     .05       0  4945.5     .05       0
Bank Sta=4927.3,4945.5
XS Rating Curve= 0 ,0
Exp/Cntr=0.3,0.1

Type RM Length L Ch R = 1 ,19086   ,60,60,60
BEGIN DESCRIPTION:
Mapping XS 9cf1aa75
END DESCRIPTION:
XS GIS Cut Line= 4
      1606464.49      6799612.84       1607437.3      6799573.71
      1608155.61      6799547.66      1608416.04      6799521.62
#Sta/Elev= 30
    3859 1859.48  3919.6 1855.97  4029.6 1853.85    4500 1849.25  4598.2  1849.9
  4720.2 1855.39  4740.2 1855.96  4770.2  1855.6  4848.7 1850.44  4890.3 1849.17
  4900.3 1846.89  4910.3 1841.31  4920.3 1836.92  4930.4 1835.69  4961.3 1835.23
  4961.8 1834.73    4979 1834.73  4979.5 1835.23  5000.4 1835.45  5010.4 1838.57
  5030.4 1849.79  5050.4  1849.3  5160.5 1849.54  5380.7 1854.04  5450.7 1858.37
  5490.7 1864.16  5548.6 1868.21  5721.6 1873.56  5751.8 1873.88  5813.1  1872.7
#Mann= 3 ,-1 , 0
    3859     .05       0  4961.3     .05       0  4979.5     .05       0
Bank Sta=4961.3,4979.5
XS Rating Curve= 0 ,0
Exp/Cntr=0.3,0.1

Type RM Length L Ch R = 1 ,19026   ,195,195,195
BEGIN DESCRIPTION:
Mapping XS c76bd12b
END DESCRIPTION:
XS GIS Cut Line= 3
      1606481.82      6799682.28       1607524.1       6799632.3
      1608320.25      6799591.08
#Sta/Elev= 30
  3876.1 1859.12  3919.3 1856.21  4067.2 1853.42  4419.9 1849.58  4570.1 1849.85
  4580.1 1848.72  4610.1 1840.89  4620.1 1839.09  4630.1 1838.83  4660.2 1839.81
  4690.2 1842.29  4740.3 1854.11  4750.3 1855.86  4760.3 1856.29  4800.3 1854.92
  4890.4 1848.41  4970.5 1845.81  4980.6  1843.9  4990.6 1840.32  4991.5 1838.17
    4992 1837.67  5009.7 1838.17  5010.6 1842.14  5020.6  1847.4  5030.6  1848.7
  5190.8 1849.23  5381.1 1853.29  5451.2 1857.42  5486.3 1862.98  5716.8 1873.12
#Mann= 3 ,-1 , 0
  3876.1     .05       0  4991.5     .05       0  5009.7     .05       0
Bank Sta=4991.5,5009.7
XS Rating Curve= 0 ,0
Exp/Cntr=0.3,0.1

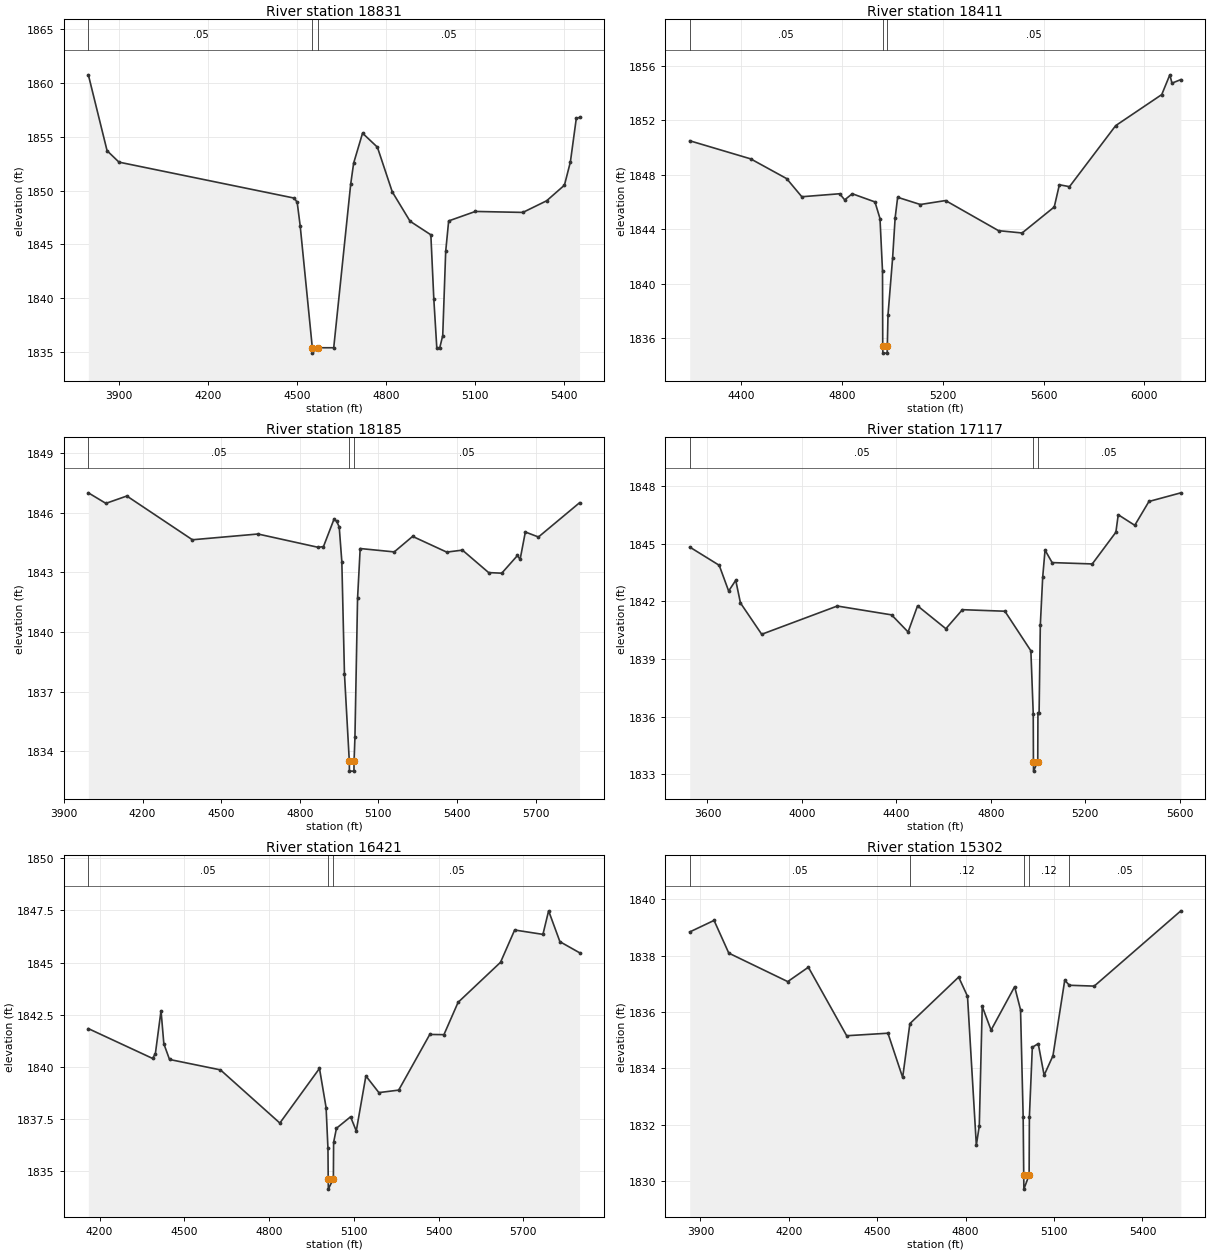
Type RM Length L Ch R = 1 ,18831   ,420,420,420
BEGIN DESCRIPTION:
Mapping XS 2e266f0a
END DESCRIPTION:
XS GIS Cut Line= 3
      1606401.92      6799782.97      1607448.15       6799821.1
      1608055.79      6799827.61
#Sta/Elev= 30
  3797.4 1860.76  3860.5 1853.71  3900.6 1852.65  4490.9 1849.31  4500.9 1848.92
    4511 1846.74  4551.9 1835.41  4552.4 1834.91  4570.1 1835.41    4624 1835.41
  4681.1 1850.59  4691.1 1852.56  4721.1 1855.34  4771.1 1854.04  4821.2 1849.89
  4881.2 1847.16  4951.2  1845.9  4961.2 1839.93  4971.2 1835.41  4981.2 1835.41
  4991.2 1836.54  5001.2 1844.36  5011.2 1847.19  5101.2 1848.07  5261.2 1847.98
  5341.2 1849.06  5401.2 1850.51  5421.2 1852.66  5441.2 1856.72    5452  1856.8
#Mann= 3 ,-1 , 0
  3797.4     .05       0  4551.9     .04       0  4570.1     .05       0
Bank Sta=4551.9,4570.1
XS Rating Curve= 0 ,0
Exp/Cntr=0.3,0.1

Type RM Length L Ch R = 1 ,18411   ,226,226,226
BEGIN DESCRIPTION:
Mapping XS b3091b88
END DESCRIPTION:
XS GIS Cut Line= 4
      1606614.83      6800042.46       1606899.1      6800135.77
      1607979.83      6800196.54      1608539.68      6800094.55
#Sta/Elev= 30
  4194.6 1850.49  4436.9 1849.16  4579.8 1847.71  4639.9 1846.38  4790.2  1846.6
  4810.2 1846.15  4840.2  1846.6  4930.4    1846  4950.4 1844.78  4960.4 1840.92
  4961.3  1835.4  4961.8  1834.9    4979  1834.9  4979.5  1835.4  4982.2  1837.7
  5000.5 1841.87  5010.5 1844.82  5020.5 1846.34  5110.7 1845.81  5210.8  1846.1
  5421.2 1843.89  5514.8 1843.72  5642.5 1845.63  5662.8 1847.26    5703 1847.12
  5886.4  1851.6  6069.4 1853.88  6101.5 1855.33    6110 1854.72  6145.3 1854.98
#Mann= 3 ,-1 , 0
  4194.6     .05       0  4961.3     .06       0  4979.5     .05       0
Bank Sta=4961.3,4979.5
XS Rating Curve= 0 ,0
Exp/Cntr=0.3,0.1

Type RM Length L Ch R = 1 ,18185   ,1068,1068,1068
BEGIN DESCRIPTION:
Elm 01 91 18185.38
END DESCRIPTION:
XS GIS Cut Line= 3
      1606398.14      6800364.27      1607405.13      6800390.31
      1608271.63      6800411.97
#Sta/Elev= 30
  3993.3    1847  4060.2 1846.47  4140.2 1846.84  4390.3 1844.64  4640.4 1844.93
  4870.5 1844.26  4890.5  1844.3  4930.5 1845.67  4940.5 1845.57  4950.5 1845.29
  4960.5 1843.54  4970.5  1837.9    4989 1833.51  4989.5 1833.01  5006.7 1833.01
  5007.2 1833.51  5010.5 1834.71  5020.5 1841.69  5030.5  1844.2  5160.5 1844.03
  5230.6 1844.81  5360.6 1844.02  5420.6 1844.12  5520.7 1842.99  5570.7 1842.96
  5630.7 1843.85  5640.7 1843.65  5660.7 1845.03  5710.7 1844.78  5867.4  1846.5
#Mann= 3 ,-1 , 0
  3993.3     .05       0    4989     .04       0  5007.2     .05       0
Bank Sta=4989,5007.2
XS Rating Curve= 0 ,0
Exp/Cntr=0.3,0.1

Type RM Length L Ch R = 1 ,17117   ,696,696,696
BEGIN DESCRIPTION:
Elm 01 91 17117.38
END DESCRIPTION:
XS GIS Cut Line= 3
      1606730.04      6800966.14      1608209.82      6800965.31
      1608810.24      6800965.31
#Sta/Elev= 30
  3524.8 1844.83  3649.8 1843.88  3689.8 1842.54  3719.8  1843.1  3739.8 1841.92
  3829.8 1840.29  4149.8 1841.76  4379.8  1841.3  4449.8 1840.41  4489.8 1841.77
  4609.8 1840.58  4679.8 1841.57  4859.8 1841.49  4969.8 1839.43  4979.8 1836.16
  4980.6 1833.67  4981.1 1833.17  4998.9 1833.67  4999.7 1836.18  5004.6 1836.18
  5009.8 1840.77  5019.8 1843.25  5029.8 1844.67  5059.8 1844.02  5229.8 1843.95
  5329.8  1845.6  5339.8 1846.51  5409.8 1845.96  5469.8  1847.2    5605 1847.65
#Mann= 3 ,-1 , 0
  3524.8     .05       0  4980.6     .05       0  4998.9     .05       0
Bank Sta=4980.6,4998.9
XS Rating Curve= 0 ,0
Exp/Cntr=0.3,0.1

Type RM Length L Ch R = 1 ,16421   ,1119,1119,1119
BEGIN DESCRIPTION:
Elm 01 91 16420.72
END DESCRIPTION:
XS GIS Cut Line= 3
       1606918.1       6801479.2      1607758.43      6801430.59
      1608654.28      6801381.97
#Sta/Elev= 30
  4160.1 1841.83  4387.4  1840.4  4397.4 1840.63  4417.4 1842.69  4427.4  1841.1
  4447.5 1840.35  4627.8 1839.85  4838.1  1837.3  4978.4 1839.92  5001.8 1838.04
  5008.4 1836.08  5009.3 1834.63  5009.8 1834.13  5027.6 1834.63  5028.4 1836.37
  5038.5 1837.05  5088.5  1837.6  5108.6 1836.92  5142.7 1839.56  5188.7 1838.76
  5258.8 1838.88  5368.9 1841.55    5419 1841.54  5469.1 1843.09  5619.3 1845.01
  5669.4 1846.56  5769.5 1846.35  5789.6 1847.48  5829.6    1846    5899 1845.47
#Mann= 3 ,-1 , 0
  4160.1     .05       0  5009.3     .05       0  5027.6     .05       0
Bank Sta=5009.3,5027.6
XS Rating Curve= 0 ,0
Exp/Cntr=0.3,0.1

Type RM Length L Ch R = 1 ,15302   ,607,607,607
BEGIN DESCRIPTION:
Elm 01 91 15302.18
END DESCRIPTION:
XS GIS Cut Line= 3
      1607172.34      6801996.79      1608307.74      6801989.85
      1608838.97       6801982.9
#Sta/Elev= 30
  3863.5 1838.84  3946.2 1839.25  3996.2 1838.09  4196.2 1837.08  4266.2 1837.59
  4396.2 1835.16  4536.2 1835.25  4586.2 1833.68  4610.7 1835.59  4776.2 1837.24
  4806.2 1836.56  4836.2 1831.28  4846.2 1831.96  4856.2  1836.2  4886.2 1835.36
  4966.2  1836.9  4986.2 1836.08  4995.1 1832.27    4997 1830.22  4997.5 1829.72
  5015.3 1830.22  5016.2 1832.28  5026.2 1834.75  5046.2 1834.88  5066.2 1833.76
  5096.2 1834.45  5136.2 1837.13  5151.9 1836.95  5236.2 1836.92  5530.2 1839.59
#Mann= 5 ,-1 , 0
  3863.5     .05       0  4610.7     .12       0    4997     .07       0
  5015.3     .12       0  5151.9     .05       0
Bank Sta=4997,5015.3
XS Rating Curve= 0 ,0
Exp/Cntr=0.3,0.1

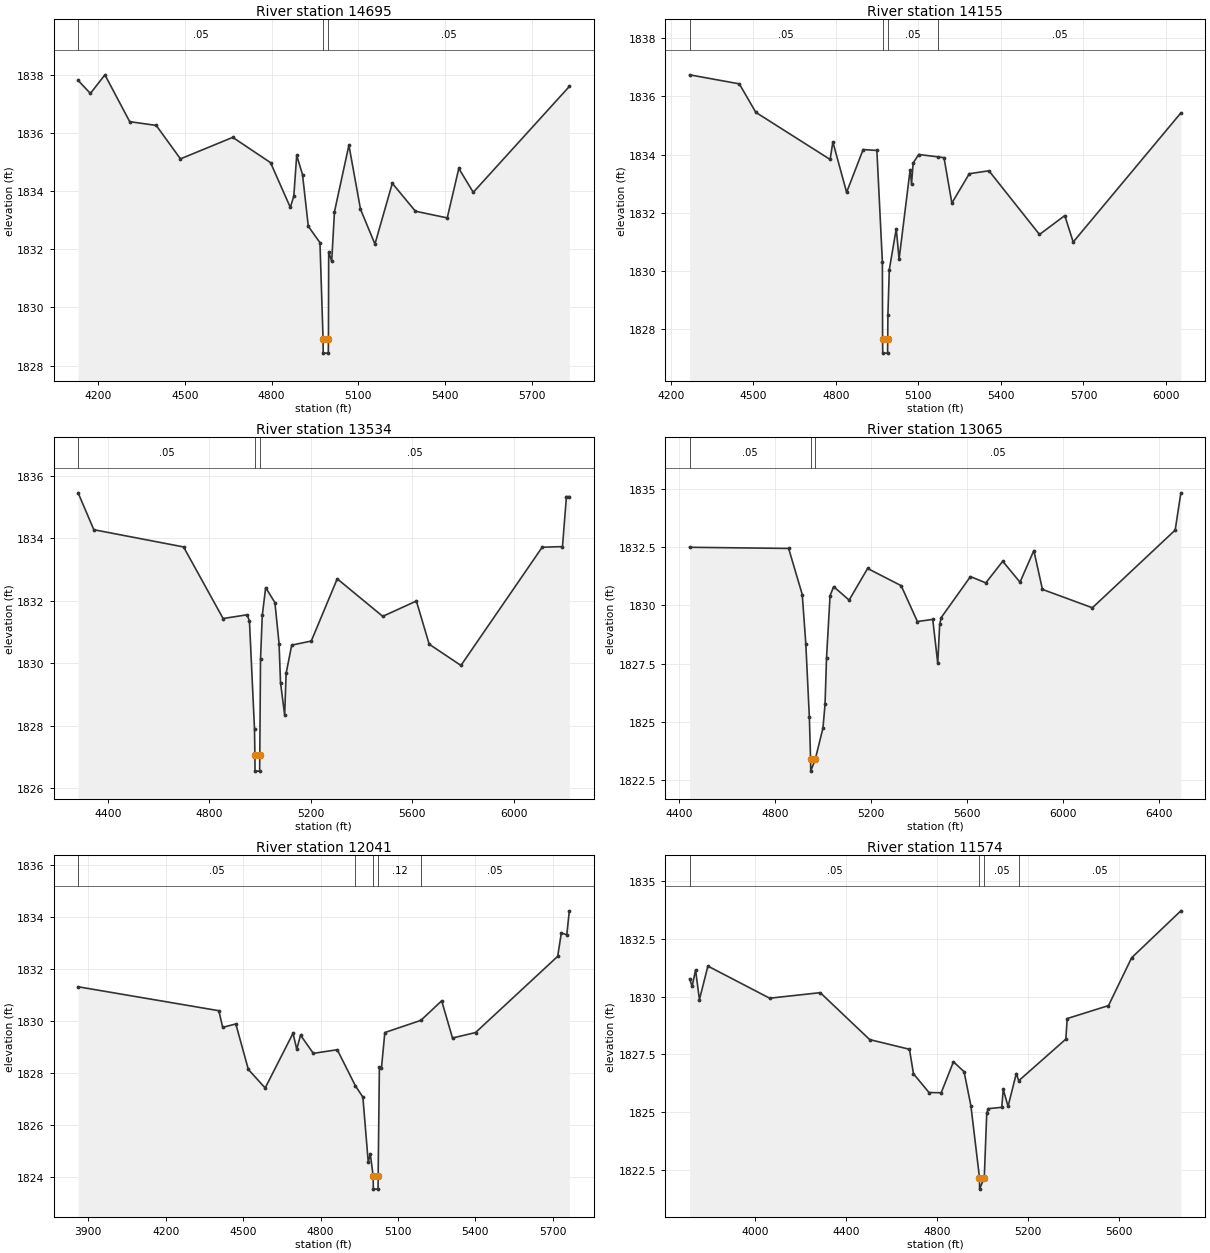
Type RM Length L Ch R = 1 ,14695   ,540,540,540
BEGIN DESCRIPTION:
Elm 01 91 14694.5
END DESCRIPTION:
XS GIS Cut Line= 3
      1607182.76       6802382.2      1608050.79      6802288.46
      1608877.19      6802253.73
#Sta/Elev= 30
  4130.6 1837.81  4173.1 1837.36  4223.4    1838  4309.2 1836.39    4401 1836.26
  4484.9 1835.11  4665.9 1835.85  4796.7 1834.98  4865.2 1833.44  4877.2 1833.83
  4887.2 1835.23  4907.3 1834.57  4927.4 1832.79  4967.7 1832.23  4978.4 1828.93
  4978.9 1828.43  4996.6 1828.43  4997.1 1828.93  4997.9 1831.91  5008.3 1831.59
  5017.9 1833.29  5067.9 1835.58    5108 1833.38    5158 1832.18  5218.1 1834.27
  5298.1 1833.31  5408.2 1833.08  5448.3 1834.78  5498.3 1833.96  5830.8  1837.6
#Mann= 3 ,-1 , 0
  4130.6     .05       0  4978.4     .05       0  4997.1     .05       0
Bank Sta=4978.4,4997.1
XS Rating Curve= 0 ,0
Exp/Cntr=0.3,0.1

Type RM Length L Ch R = 1 ,14155   ,621,621,621
BEGIN DESCRIPTION:
Elm 01 91 14154.67
END DESCRIPTION:
XS GIS Cut Line= 3
       1607144.5      6802705.12      1607870.24      6802719.01
      1608908.38      6802507.22
#Sta/Elev= 30
  4268.6 1836.74  4449.1 1836.43  4509.1 1835.45  4779.2 1833.83  4789.2 1834.43
  4839.2  1832.7  4899.2 1834.17  4949.2 1834.14  4969.2  1830.3  4969.9 1827.67
  4970.4 1827.17  4988.1 1827.17  4988.6 1827.67  4989.2 1828.48  4994.3 1830.04
  5019.6 1831.45  5029.9  1830.4  5070.1 1833.48  5075.2 1832.99    5081 1833.71
  5101.4    1834  5170.9 1833.92  5193.2 1833.89  5221.7 1832.33  5285.1 1833.34
  5356.5 1833.44  5540.2 1831.25  5632.1  1831.9  5662.7 1830.99    6054 1835.43
#Mann= 4 ,-1 , 0
  4268.6     .05       0  4969.9     .07       0  4988.6     .05       0
  5170.9     .05       0
Bank Sta=4969.9,4988.6
XS Rating Curve= 0 ,0
Exp/Cntr=0.3,0.1

Type RM Length L Ch R = 1 ,13534   ,469,469,469
BEGIN DESCRIPTION:
Elm 01 91 13534.47
END DESCRIPTION:
XS GIS Cut Line= 4
      1607264.74      6803370.93      1607957.04      6803177.78
      1608504.78      6802892.06      1609020.51      6802587.64
#Sta/Elev= 30
    4283 1835.45    4345 1834.27  4698.5 1833.72  4854.3 1831.43    4949 1831.55
  4958.1 1831.35    4978  1827.9  4979.6 1827.05  4980.1 1826.55  4998.3 1826.55
  4998.8 1827.05  5001.7 1830.12  5008.6 1831.53    5022 1832.42  5058.4 1831.94
  5074.8 1830.63  5080.5 1829.38  5096.9 1828.34  5102.6 1829.68  5124.7 1830.58
  5201.7 1830.71    5304  1832.7  5483.3  1831.5  5615.8 1831.99  5666.2 1830.61
  5791.4 1829.93  6111.4 1833.71  6191.4 1833.73    6207 1835.33  6218.4 1835.33
#Mann= 3 ,-1 , 0
    4283     .05       0  4979.6     .05       0  4998.8     .05       0
Bank Sta=4979.6,4998.8
XS Rating Curve= 0 ,0
Exp/Cntr=0.3,0.1

Type RM Length L Ch R = 1 ,13065   ,1024,1024,1024
BEGIN DESCRIPTION:
Mapping XS 0d9294b1
END DESCRIPTION:
XS GIS Cut Line= 5
      1607340.96      6803848.86      1607853.96       6803489.5
      1608054.48      6803335.86      1608421.67      6803044.19
      1608993.03      6802642.02
#Sta/Elev= 30
  4443.9  1832.5  4856.4 1832.45  4913.1 1830.47  4927.9 1828.36  4942.7  1825.2
  4947.9 1823.38  4948.4 1822.88  4967.1 1823.38  4999.4 1824.73  5008.1 1825.76
  5014.2 1827.74    5029 1830.42  5043.9 1830.81  5108.4 1830.23  5185.4 1831.59
  5325.2 1830.85  5392.8 1829.31  5456.8  1829.4  5477.7 1827.51  5485.7 1829.19
  5492.1 1829.48  5613.9 1831.24  5677.9 1830.97  5748.4  1831.9  5820.3    1831
    5878 1832.36  5913.8 1830.69  6121.9  1829.9  6466.9 1833.24  6490.5 1834.84
#Mann= 3 ,-1 , 0
  4443.9     .05       0  4947.9     .05       0  4967.1     .05       0
Bank Sta=4947.9,4967.1
XS Rating Curve= 0 ,0
Exp/Cntr=0.3,0.1

Type RM Length L Ch R = 1 ,12041   ,467,467,467
BEGIN DESCRIPTION:
Mapping XS 800fa10a
END DESCRIPTION:
XS GIS Cut Line= 5
      1607679.51       6803999.9        1608380.      6803523.36
      1608643.02      6803197.84       1608692.5      6802960.86
      1608974.41      6802683.62
#Sta/Elev= 30
  3860.6 1831.33  4405.8 1830.41  4420.8 1829.77  4471.6  1829.9  4520.3 1828.15
  4585.4 1827.44  4693.2 1829.54  4707.8 1828.93  4722.4 1829.47    4772 1828.77
  4864.7 1828.91  4935.1 1827.52  4963.9 1827.09  4984.7 1824.59  4992.7  1824.9
  5003.9 1824.05  5004.4 1823.55  5022.6 1823.55  5023.1 1824.05  5027.9 1828.25
  5035.8 1828.19    5049 1829.57  5188.8 1830.04  5269.2 1830.79  5311.2 1829.36
  5400.4 1829.57  5718.7  1832.5  5732.9  1833.4    5754 1833.33  5763.8 1834.25
#Mann= 5 ,-1 , 0
  3860.6     .05       0  4935.1     .12       0  5003.9     .07       0
  5023.1     .12       0  5188.8     .05       0
Bank Sta=5003.9,5023.1
XS Rating Curve= 0 ,0
Exp/Cntr=0.3,0.1

Type RM Length L Ch R = 1 ,11574   ,403,403,403
BEGIN DESCRIPTION:
Elm 01 91 11573.622
END DESCRIPTION:
XS GIS Cut Line= 3
      1607604.82      6804112.08        1608803.      6803643.37
      1609536.92      6803170.25
#Sta/Elev= 30
  3713.4 1830.77  3724.3 1830.44  3739.4 1831.15  3756.5 1829.87  3793.7 1831.32
  4065.2 1829.93  4287.7 1830.17  4504.9 1828.14    4680 1827.72  4697.6 1826.66
  4765.9 1825.85  4819.6 1825.84  4873.3 1827.18  4920.1 1826.75    4950 1825.28
  4987.8 1822.17  4988.3 1821.67  5008.9 1822.17  5019.7 1824.95  5026.2 1825.15
  5085.7 1825.21  5092.3 1825.99  5113.4 1825.25  5149.7 1826.67  5160.4 1826.36
  5367.5 1828.16  5373.5 1829.05    5555 1829.61  5656.8 1831.68  5873.2 1833.71
#Mann= 4 ,-1 , 0
  3713.4     .05       0  4987.8     .05       0  5008.9     .05       0
  5160.4     .05       0
Bank Sta=4987.8,5008.9
XS Rating Curve= 0 ,0
Exp/Cntr=0.3,0.1