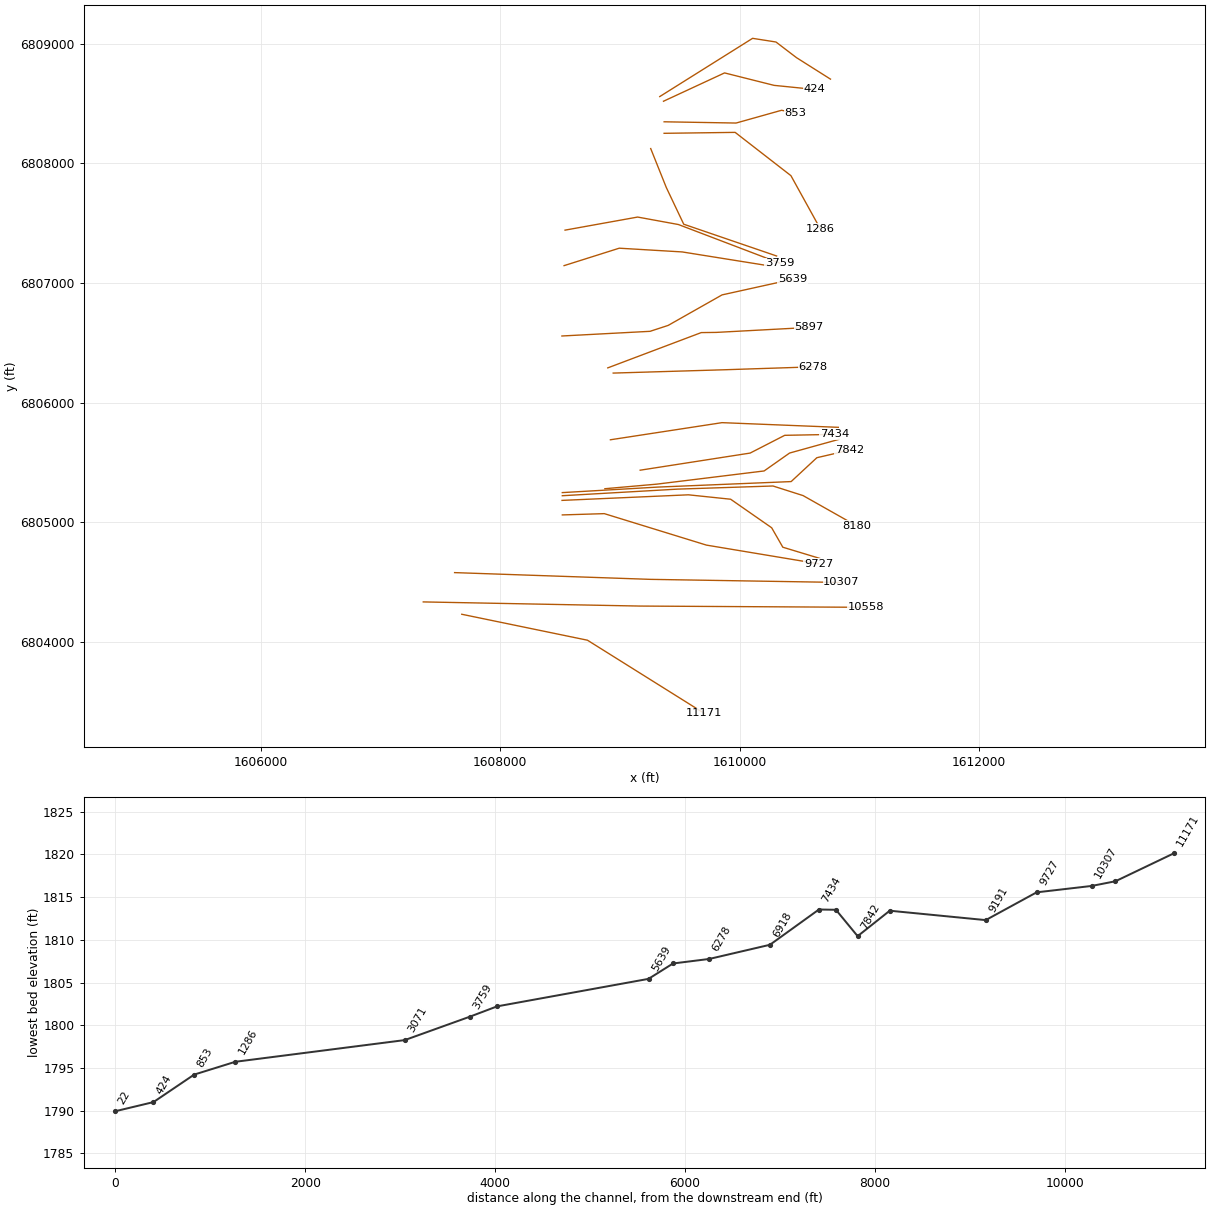
HEC-RAS study Elm 01 91.prj: Elm 01 91 Base Level Engineering

--- Elm 01 91.g01 (geometry) --- (continued)

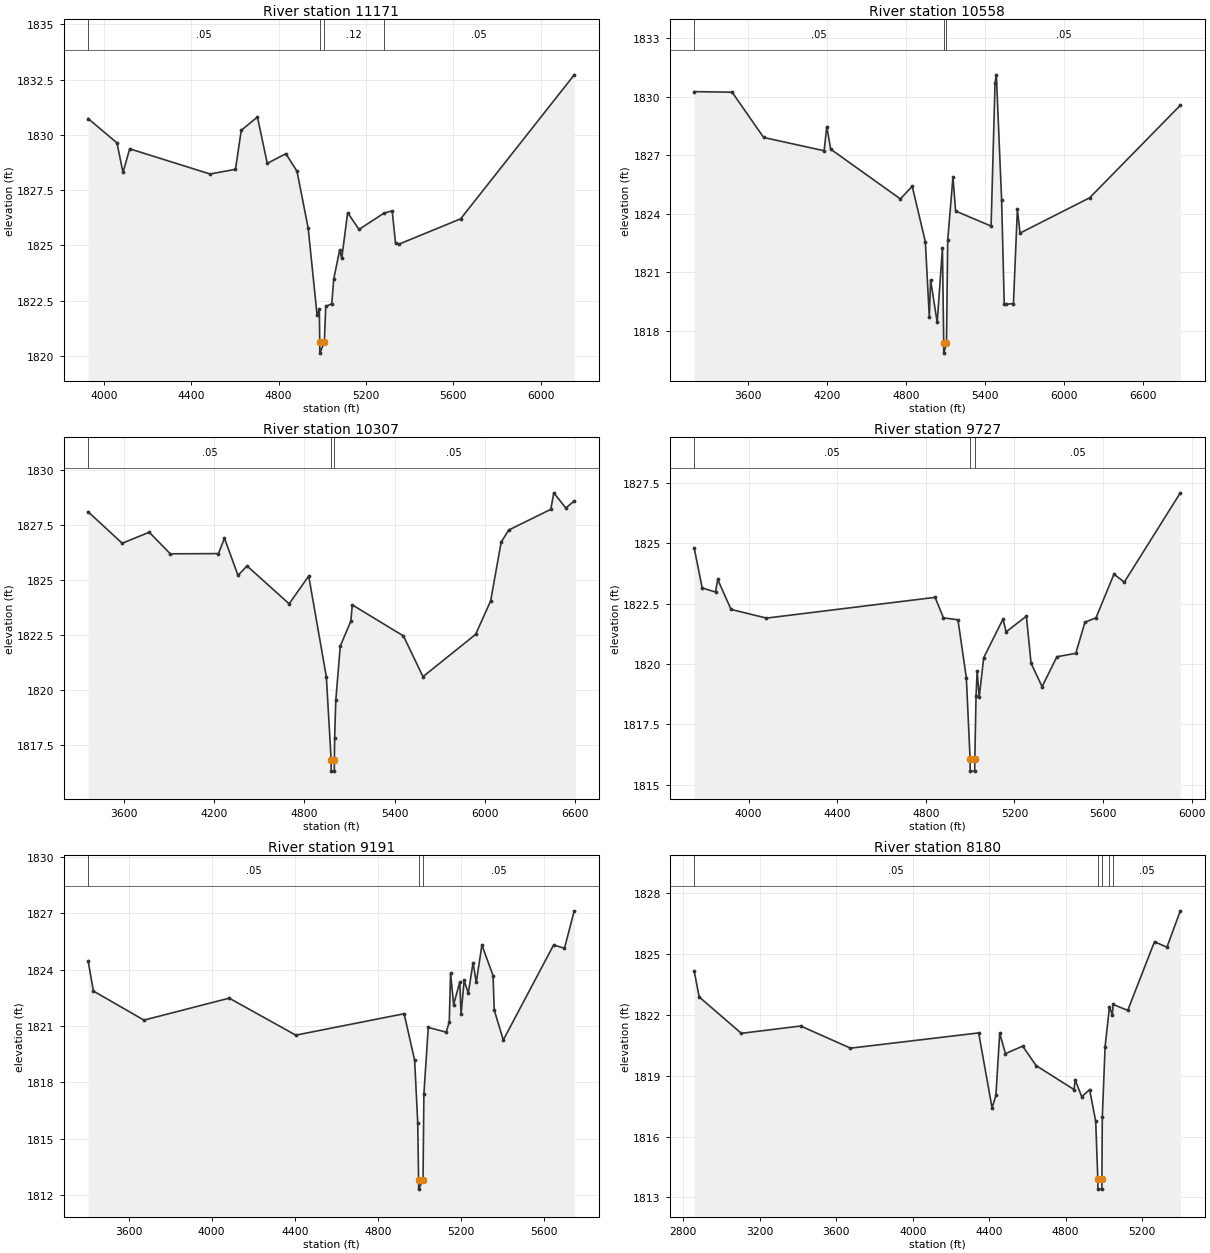
Type RM Length L Ch R = 1 ,11171   ,613,613,613
BEGIN DESCRIPTION:
Elm 01 91 11170.66
END DESCRIPTION:
XS GIS Cut Line= 3
      1607678.52      6804229.29      1608728.92      6804012.27
      1609705.52      6803400.27
#Sta/Elev= 30
  3928.5 1830.74  4060.6 1829.64  4088.3  1828.3  4118.9 1829.37  4486.5 1828.23
    4603 1828.44  4629.5 1830.21  4703.5 1830.81  4748.6 1828.71  4833.7 1829.15
  4884.8 1828.35  4935.8 1825.78  4976.7 1821.83  4986.9  1822.1  4988.7 1820.62
  4989.2 1820.12  5009.8 1820.62  5016.3 1822.24  5043.7 1822.35  5052.9 1823.48
    5080 1824.79  5089.4 1824.41  5116.5 1826.48  5168.4 1825.72  5283.1 1826.46
  5320.4 1826.56  5335.7 1825.09  5350.5 1825.05  5633.7  1826.2  6153.6 1832.72
#Mann= 4 ,-1 , 0
  3928.5     .05       0  4988.7     .05       0  5009.8     .12       0
  5283.1     .05       0
Bank Sta=4988.7,5009.8
XS Rating Curve= 0 ,0
Exp/Cntr=0.3,0.1

Type RM Length L Ch R = 1 ,10558   ,251,251,251
BEGIN DESCRIPTION:
Elm 01 91 10557.84
END DESCRIPTION:
XS GIS Cut Line= 3
      1607356.53      6804332.58      1609169.02      6804297.86
      1611054.47      6804287.44
#Sta/Elev= 30
  3188.8 1830.26  3477.3 1830.23  3717.4 1827.91  4177.5 1827.23  4197.5 1828.47
  4227.5 1827.31  4757.6 1824.76  4847.6 1825.41  4947.6 1822.56  4977.6 1818.71
  4987.6  1820.6  5037.6 1818.43  5077.6 1822.25  5087.1 1817.36  5087.6 1816.86
  5108.2 1817.36  5117.6 1822.64  5157.6 1825.88  5177.6 1824.14  5447.6 1823.37
  5477.6 1830.71  5487.6 1831.12  5527.6 1824.72  5547.6 1819.39  5557.6 1819.36
  5617.6  1819.4  5647.6 1824.23  5667.6 1823.01  6197.6 1824.82  6887.1 1829.56
#Mann= 3 ,-1 , 0
  3188.8     .05       0  5087.1     .03       0  5108.2     .05       0
Bank Sta=5087.1,5108.2
XS Rating Curve= 0 ,0
Exp/Cntr=0.3,0.1

Type RM Length L Ch R = 1 ,10307   ,580,580,580
BEGIN DESCRIPTION:
Elm 01 91 10306.82
END DESCRIPTION:
XS GIS Cut Line= 3
      1607618.51       6804577.7      1609254.78      6804521.28
      1610851.02      6804495.25
#Sta/Elev= 30
    3361 1828.09  3587.6 1826.66  3767.7 1827.16  3907.8 1826.18    4228 1826.19
    4268 1826.89  4358.1  1825.2  4418.1 1825.63  4698.3 1823.91  4828.4 1825.17
  4945.8 1820.59  4977.8 1816.81  4978.3 1816.31  4998.6 1816.31  4999.1 1816.81
  5000.9  1817.8  5008.5 1819.52  5038.5 1821.99  5108.5 1823.12  5118.5 1823.86
  5458.5 1822.45  5588.5  1820.6  5938.6 1822.52  6038.6 1824.04  6108.6 1826.71
  6158.6 1827.26  6438.7  1828.2  6458.7 1828.95  6538.7 1828.26  6594.7 1828.58
#Mann= 3 ,-1 , 0
    3361     .05       0  4977.8     .05       0  4999.1     .05       0
Bank Sta=4977.8,4999.1
XS Rating Curve= 0 ,0
Exp/Cntr=0.3,0.1

Type RM Length L Ch R = 1 ,9727    ,536,536,536
BEGIN DESCRIPTION:
Elm 01 91 9727.4
END DESCRIPTION:
XS GIS Cut Line= 4
      1608518.72      6805060.26      1608869.59      6805070.98
      1609723.53      6804807.73      1610660.47      6804651.58
#Sta/Elev= 30
  3754.4 1824.81  3790.7 1823.15  3850.7 1822.98  3860.7  1823.5  3920.8 1822.26
  4080.8  1821.9  4841.9 1822.76  4879.8 1821.91  4945.1 1821.83    4983 1819.43
    5000 1816.06  5000.5 1815.56  5020.8 1815.56  5021.3 1816.06  5026.8 1818.68
  5031.9 1819.71  5041.1 1818.62  5061.4 1820.26  5148.5 1821.86  5162.7 1821.33
    5254 1821.98  5275.2 1820.03  5324.9 1819.06  5391.8  1820.3    5477 1820.44
  5518.5 1821.73  5568.2 1821.91  5649.4 1823.72    5696 1823.39  5948.9 1827.09
#Mann= 3 ,-1 , 0
  3754.4     .05       0    5000     .05       0  5021.3     .05       0
Bank Sta=5000,5021.3
XS Rating Curve= 0 ,0
Exp/Cntr=0.3,0.1

Type RM Length L Ch R = 1 ,9191    ,1011,1011,1011
BEGIN DESCRIPTION:
Mapping XS fca7e6ed
END DESCRIPTION:
XS GIS Cut Line= 6
      1608516.54      6805181.79      1609572.67      6805228.44
      1609925.68      6805191.54      1610268.57      6804952.83
      1610361.88      6804790.07      1610670.03      6804696.76
#Sta/Elev= 30
  3405.4 1824.47  3430.9 1822.86  3674.1 1821.31  4084.5 1822.48  4404.8 1820.51
  4926.3 1821.65  4976.8 1819.17  4991.7 1815.85  4995.8 1812.81  4996.3 1812.31
  5017.2 1812.81  5021.3 1817.36  5042.3 1820.92  5128.7 1820.67  5143.5 1821.21
  5149.6 1823.81  5164.5 1822.14  5194.1 1823.34  5200.2 1821.62  5215.1 1823.42
  5235.1 1822.74  5257.9 1824.37  5273.4 1823.32  5300.5 1825.31  5354.2 1823.68
  5359.9 1821.85  5403.3 1820.25  5645.6 1825.31  5697.9 1825.14  5744.9 1827.13
#Mann= 3 ,-1 , 0
  3405.4     .05       0  4995.8     .05       0  5017.2     .05       0
Bank Sta=4995.8,5017.2
XS Rating Curve= 0 ,0
Exp/Cntr=0.3,0.1

Type RM Length L Ch R = 1 ,8180    ,338,338,338
BEGIN DESCRIPTION:
Mapping XS c83c849c
END DESCRIPTION:
XS GIS Cut Line= 5
      1608518.78      6805220.85      1609481.65      6805276.04
      1610279.42      6805302.22      1610531.15      6805221.93
      1610980.21      6804968.11
#Sta/Elev= 30
    2857 1824.15  2883.3 1822.87  3103.6 1821.08    3414 1821.44  3674.6 1820.35
  4345.1  1821.1  4415.1 1817.41  4435.1 1818.02  4455.1 1821.08  4485.2 1820.08
  4575.2 1820.45  4645.6 1819.49  4844.1 1818.31  4849.3  1818.8  4883.9 1817.96
  4925.4 1818.31  4957.2 1816.75  4968.2 1813.91  4968.7 1813.41  4989.1 1813.41
  4989.6 1813.91  4991.7 1816.95  5006.3 1820.43  5029.3 1822.39  5043.8 1821.99
  5048.6  1822.5  5124.7 1822.21  5264.7 1825.59  5329.7 1825.32  5399.7 1827.11
#Mann= 5 ,-1 , 0
    2857     .05       0  4968.2     .05       0  4989.6     .05       0
  5029.3     .12       0  5048.6     .05       0
Bank Sta=4968.2,4989.6
XS Rating Curve= 0 ,0
Exp/Cntr=0.3,0.1

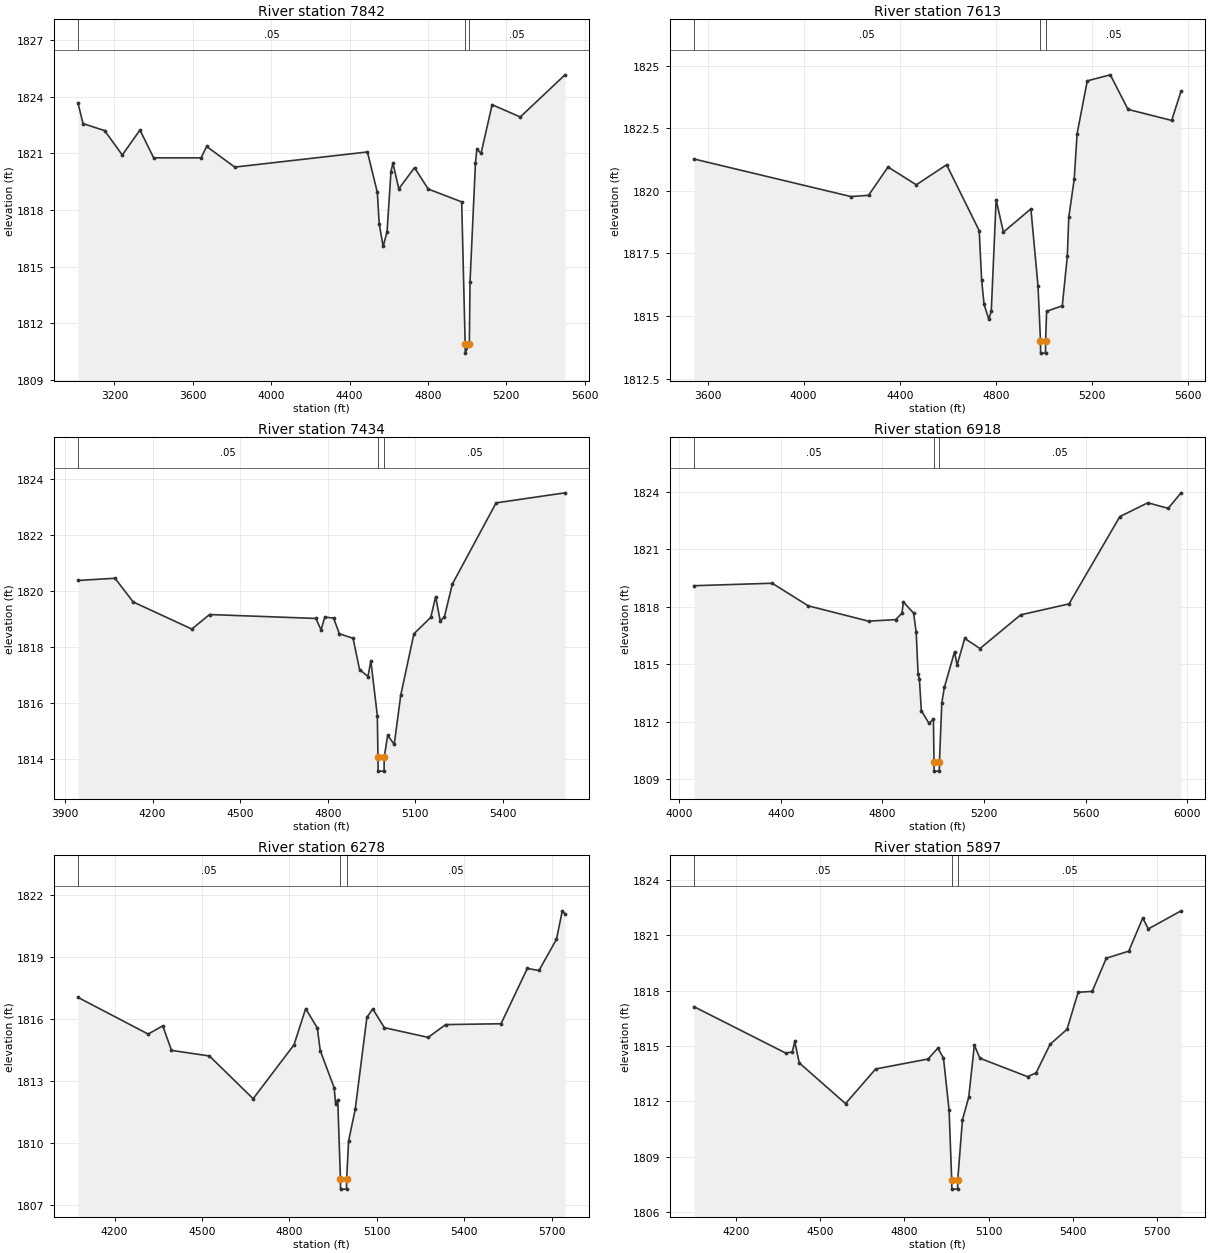
Type RM Length L Ch R = 1 ,7842    ,229,229,229
BEGIN DESCRIPTION:
Mapping XS d580d016
END DESCRIPTION:
XS GIS Cut Line= 5
      1608518.73      6805246.89      1609321.09      6805293.29
      1610431.33      6805339.11      1610646.17      6805538.77
      1610917.39      6805601.69
#Sta/Elev= 30
  3013.4 1823.67  3039.7 1822.57  3149.9  1822.2    3240 1820.91  3330.2 1822.23
  3400.3 1820.76  3642.3 1820.76  3670.8 1821.36  3814.1 1820.27  4491.6 1821.07
  4542.1 1818.93  4551.6 1817.28  4571.7 1816.07  4591.7 1816.85  4611.7 1820.03
  4621.7 1820.48  4651.7 1819.12  4731.8 1820.24  4801.8 1819.11  4972.7 1818.43
  4990.4 1810.93  4990.9 1810.43  5011.8 1810.93  5015.2 1814.19  5043.1 1820.51
  5050.4 1821.23  5071.4 1820.99  5128.1 1823.57  5271.7 1822.92    5500 1825.15
#Mann= 3 ,-1 , 0
  3013.4     .05       0  4990.4     .05       0  5011.8     .05       0
Bank Sta=4990.4,5011.8
XS Rating Curve= 0 ,0
Exp/Cntr=0.3,0.1

Type RM Length L Ch R = 1 ,7613    ,179,179,179
BEGIN DESCRIPTION:
Mapping XS 007dd90f
END DESCRIPTION:
XS GIS Cut Line= 5
       1608874.6      6805279.44      1609308.49      6805317.73
      1610205.63      6805428.09      1610418.31      6805577.83
      1610831.41      6805692.46
#Sta/Elev= 30
  3543.4 1821.27  4197.1 1819.77  4270.3 1819.82  4351.5 1820.95  4469.2 1820.24
  4595.3 1821.04  4731.1 1818.41  4741.2 1816.45  4751.3 1815.47  4771.4 1814.87
  4781.5 1815.22  4801.6 1819.64  4831.9 1818.35  4946.4 1819.28    4976  1816.2
  4986.3 1814.02  4986.8 1813.52  5007.2 1813.52  5007.7 1814.02  5011.8 1815.19
  5077.1 1815.41    5098 1817.38  5104.1 1818.94  5126.7 1820.46  5138.8 1822.28
  5181.1 1824.39  5277.1 1824.63  5350.8 1823.25  5532.5 1822.81  5571.7 1823.98
#Mann= 3 ,-1 , 0
  3543.4     .05       0  4986.3     .05       0  5007.7     .05       0
Bank Sta=4986.3,5007.7
XS Rating Curve= 0 ,0
Exp/Cntr=0.3,0.1

Type RM Length L Ch R = 1 ,7434    ,516,516,516
BEGIN DESCRIPTION:
Mapping XS e9dd738d
END DESCRIPTION:
XS GIS Cut Line= 4
      1609169.42      6805434.39      1610088.66      6805577.61
      1610377.72      6805726.05      1610790.87      6805733.84
#Sta/Elev= 30
  3944.2 1820.38  4071.3 1820.46  4133.6 1819.61  4334.4 1818.64  4395.2 1819.16
  4759.5 1819.02  4777.2 1818.61  4789.9 1819.07  4820.2 1819.03    4840 1818.47
  4886.8 1818.31    4909 1817.19  4937.9 1816.94  4947.7  1817.5  4969.9 1815.54
  4972.1 1814.05  4972.6 1813.55    4993 1813.55  4993.5 1814.05  5005.3 1814.83
  5027.8 1814.51  5050.3 1816.28  5095.2 1818.47    5153 1819.06  5169.6  1819.8
  5185.2 1818.94  5199.5 1819.07  5226.8 1820.25  5376.8 1823.16  5612.7 1823.52
#Mann= 3 ,-1 , 0
  3944.2     .05       0  4972.1     .05       0  4993.5     .05       0
Bank Sta=4972.1,4993.5
XS Rating Curve= 0 ,0
Exp/Cntr=0.3,0.1

Type RM Length L Ch R = 1 ,6918    ,640,640,640
BEGIN DESCRIPTION:
Elm 01 91 6918.28
END DESCRIPTION:
XS GIS Cut Line= 3
      1608920.62      6805688.82      1609853.74      6805832.04
      1610825.71      6805792.99
#Sta/Elev= 30
  4058.3  1819.1  4366.2 1819.23  4507.9 1818.05  4745.3 1817.25  4851.9 1817.33
    4877 1817.67  4882.2 1818.25  4922.7 1817.67  4932.8 1816.66  4940.3 1814.47
  4945.4 1814.23    4953 1812.58  4983.4 1811.91  5000.5 1812.15  5002.9 1809.92
  5003.4 1809.42  5023.8 1809.42  5024.3 1809.92  5033.6 1812.98  5043.6 1813.79
  5083.7 1815.65  5093.7 1814.95  5123.7 1816.35  5183.8 1815.82  5343.9 1817.58
    5534 1818.15  5734.2 1822.71  5844.3 1823.43  5924.4 1823.14  5975.1 1823.95
#Mann= 3 ,-1 , 0
  4058.3     .05       0  5002.9     .05       0  5024.3     .05       0
Bank Sta=5002.9,5024.3
XS Rating Curve= 0 ,0
Exp/Cntr=0.3,0.1

Type RM Length L Ch R = 1 ,6278    ,381,381,381
BEGIN DESCRIPTION:
Elm 01 91 6277.69
END DESCRIPTION:
XS GIS Cut Line= 3
      1608944.06      6806246.68      1609874.57      6806274.46
      1610614.15      6806298.76
#Sta/Elev= 30
  4074.3 1817.05  4315.3 1815.27  4365.4 1815.67  4395.4 1814.48  4525.4 1814.21
  4675.5 1812.14  4815.6 1814.75  4855.6  1816.5  4895.6 1815.57  4905.6 1814.47
  4953.5 1812.67  4958.5 1811.86  4965.6  1812.1  4974.9 1808.26  4975.4 1807.76
  4995.8 1807.76  4996.3 1808.26  5002.9 1810.09  5025.7 1811.63  5065.7 1816.08
  5085.7 1816.49  5125.7 1815.58  5275.8 1815.11  5335.8 1815.73  5525.9 1815.77
    5616 1818.45    5656 1818.35    5716 1819.86    5736 1821.24  5745.2 1821.09
#Mann= 3 ,-1 , 0
  4074.3     .05       0  4974.9     .05       0  4996.3     .05       0
Bank Sta=4974.9,4996.3
XS Rating Curve= 0 ,0
Exp/Cntr=0.3,0.1

Type RM Length L Ch R = 1 ,5897    ,258,258,258
BEGIN DESCRIPTION:
Elm 01 91 5898.44
END DESCRIPTION:
XS GIS Cut Line= 4
      1608898.67      6806290.23      1609679.91      6806585.36
      1609805.12      6806586.96      1610581.46      6806628.55
#Sta/Elev= 30
    4049 1817.13  4376.5 1814.61  4399.8 1814.68  4408.5 1815.24  4424.6 1814.08
  4589.7 1811.87  4697.2 1813.75  4884.1 1814.29  4919.2 1814.88  4939.2 1814.34
  4959.2 1811.51  4968.5 1807.73    4969 1807.23  4989.5 1807.23    4990 1807.73
  5006.8 1810.99  5029.3 1812.22  5049.3 1815.04  5069.3 1814.33  5239.6 1813.33
  5269.6 1813.54  5319.7 1815.09  5379.8  1815.9  5419.8 1817.91  5469.9 1817.96
    5520 1819.76  5600.1 1820.14  5650.1 1821.94  5670.2 1821.35  5786.8 1822.33
#Mann= 3 ,-1 , 0
    4049     .05       0  4968.5     .05       0    4990     .05       0
Bank Sta=4968.5,4990
XS Rating Curve= 0 ,0
Exp/Cntr=0.3,0.1

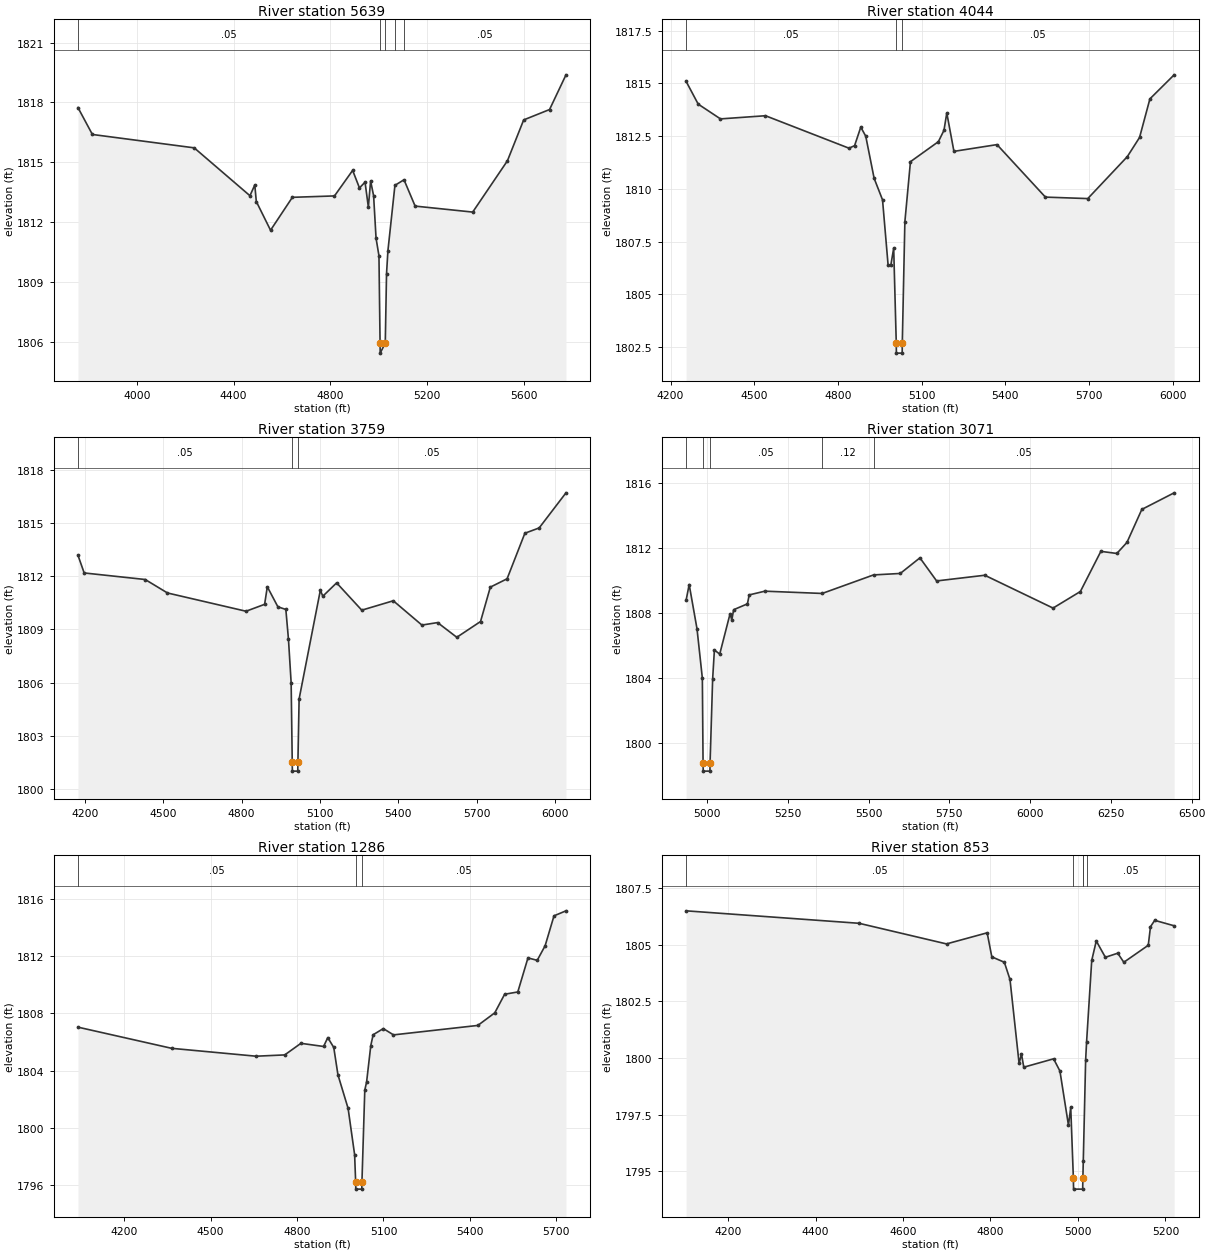
Type RM Length L Ch R = 1 ,5639    ,1595,1595,1595
BEGIN DESCRIPTION:
Mapping XS 93ff9285
END DESCRIPTION:
XS GIS Cut Line= 5
      1608515.38      6806556.93      1609252.39        6806596.
      1609403.44      6806645.48      1609853.96      6806900.68
      1610441.28      6807030.62
#Sta/Elev= 30
    3757 1817.74  3816.7 1816.39  4237.3 1815.72  4467.6 1813.32  4487.6 1813.86
  4493.9 1813.03  4552.7 1811.59  4642.9 1813.24  4816.9 1813.31  4891.9 1814.59
  4920.1 1813.71  4943.1    1814  4956.8 1812.75  4966.1 1814.06  4978.5 1813.32
  4988.6 1811.19  5000.6 1810.31  5005.2 1805.93  5005.7 1805.43  5026.7 1805.93
  5031.9 1809.41  5037.6 1810.56  5066.6 1813.84  5104.1 1814.12    5150  1812.8
  5387.9  1812.5  5531.3 1815.07  5598.5 1817.12  5705.4 1817.64  5773.3 1819.38
#Mann= 5 ,-1 , 0
    3757     .05       0  5005.2     .05       0  5026.7     .05       0
  5066.6     .12       0  5104.1     .05       0
Bank Sta=5005.2,5026.7
XS Rating Curve= 0 ,0
Exp/Cntr=0.3,0.1

Type RM Length L Ch R = 1 ,4044    ,285,285,285
BEGIN DESCRIPTION:
Mapping XS a13c5d73
END DESCRIPTION:
XS GIS Cut Line= 4
      1608533.65      6807145.48      1608994.58      6807291.31
      1609520.62      6807260.06       1610250.8      6807143.13
#Sta/Elev= 30
  4255.9  1815.1  4299.3 1814.02  4379.1 1813.32  4540.5 1813.47  4839.9 1811.93
    4860 1812.05  4882.2 1812.93    4900  1812.5  4930.1  1810.5  4960.2 1809.48
  4980.2 1806.38  4990.2  1806.4  5000.2 1807.19  5009.4 1802.71  5009.9 1802.21
  5030.6 1802.21  5031.1 1802.71  5040.3 1808.44  5060.3 1811.29  5160.5 1812.24
  5180.5 1812.78  5190.6  1813.6  5216.2 1811.78  5370.6  1812.1  5544.2 1809.61
  5696.1 1809.54  5837.9 1811.53  5881.8 1812.44  5918.9 1814.27  6005.8 1815.41
#Mann= 3 ,-1 , 0
  4255.9     .05       0  5009.4     .05       0  5031.1     .05       0
Bank Sta=5009.4,5031.1
XS Rating Curve= 0 ,0
Exp/Cntr=0.3,0.1

Type RM Length L Ch R = 1 ,3759    ,688,688,688
BEGIN DESCRIPTION:
Mapping XS 9552f367
END DESCRIPTION:
XS GIS Cut Line= 4
      1608541.44      6807442.35      1609148.23      6807551.73
      1609489.37      6807489.23      1610335.77      6807166.29
#Sta/Elev= 30
  4173.3 1813.19  4197.2 1812.19  4430.9 1811.82  4516.3 1811.06  4817.1 1810.03
  4888.3 1810.42  4898.6 1811.41  4939.1 1810.28  4969.6 1810.13  4979.7 1808.44
  4989.9 1805.99  4994.1 1801.51  4994.6 1801.01  5015.3 1801.01  5015.8 1801.51
  5020.4 1805.08  5101.7 1811.21  5111.3 1810.88  5164.1 1811.63  5260.4 1810.09
  5381.1 1810.62  5490.7 1809.25  5550.8 1809.39  5624.4 1808.56  5715.3 1809.45
  5752.8 1811.39    5817 1811.86  5885.1 1814.43  5939.9 1814.73  6042.6 1816.71
#Mann= 3 ,-1 , 0
  4173.3     .05       0  4994.1     .05       0  5015.8     .05       0
Bank Sta=4994.1,5015.8
XS Rating Curve= 0 ,0
Exp/Cntr=0.3,0.1

Type RM Length L Ch R = 1 ,3071    ,1785,1785,1785
BEGIN DESCRIPTION:
Mapping XS 3b7e8a69
END DESCRIPTION:
XS GIS Cut Line= 4
      1609257.59      6808124.66      1609387.81      6807799.12
      1609533.64      6807491.83      1610309.69       6807226.2
#Sta/Elev= 30
  4934.8 1808.77  4944.3 1809.74  4968.6 1807.01  4985.1 1803.98  4987.3 1798.76
  4987.8 1798.26  5008.5 1798.26    5009 1798.76    5017 1803.94  5022.4 1805.71
  5038.9 1805.46  5070.9 1807.94  5076.3 1807.56    5082 1808.19  5124.7 1808.55
  5130.1  1809.1  5178.6 1809.33  5356.1 1809.19  5515.1 1810.33  5597.9 1810.42
  5658.7 1811.38  5710.4 1809.96  5859.5 1810.31  6070.9 1808.29  6155.5 1809.31
  6218.9 1811.78  6268.4 1811.65  6299.7 1812.33  6345.7 1814.36  6445.8 1815.38
#Mann= 5 ,-1 , 0
  4934.8     .05       0  4987.3     .05       0    5009     .05       0
  5356.1     .12       0  5515.1     .05       0
Bank Sta=4987.3,5009
XS Rating Curve= 0 ,0
Exp/Cntr=0.3,0.1

Type RM Length L Ch R = 1 ,1286    ,433,433,433
BEGIN DESCRIPTION:
Mapping XS 5420630f
END DESCRIPTION:
XS GIS Cut Line= 4
      1609369.56      6808252.25      1609963.33      6808260.06
      1610429.48      6807898.08      1610676.09      6807451.57
#Sta/Elev= 30
  4039.5 1807.04    4365 1805.56  4657.8 1805.01  4757.3  1805.1  4813.5 1805.91
  4892.2 1805.69  4906.7 1806.31  4927.5 1805.62    4942 1803.71  4977.3 1801.36
  4999.9 1798.13  5003.5 1796.22    5004 1795.72  5024.8 1795.72  5025.3 1796.22
  5035.2 1802.64  5041.5 1803.21    5056 1805.75  5064.2 1806.51  5099.5 1806.94
  5134.8  1806.5  5427.5 1807.16  5486.4 1808.04  5520.6 1809.34  5566.3  1809.5
  5601.6 1811.88  5633.7 1811.71  5661.2 1812.73    5692 1814.82  5733.6 1815.17
#Mann= 3 ,-1 , 0
  4039.5     .05       0  5003.5     .05       0  5025.3     .05       0
Bank Sta=5003.5,5025.3
XS Rating Curve= 0 ,0
Exp/Cntr=0.3,0.1

Type RM Length L Ch R = 1 ,853     ,429,429,429
BEGIN DESCRIPTION:
Mapping XS d848157d
END DESCRIPTION:
XS GIS Cut Line= 4
      1609369.58       6808348.6      1609971.14      6808338.18
      1610351.35      6808444.95      1610468.57      6808421.51
#Sta/Elev= 30
  4103.9  1806.5  4499.4 1805.95  4699.4 1805.04  4792.4 1805.53    4803 1804.47
  4831.7 1804.23  4844.6 1803.47  4865.4 1799.77  4870.9 1800.18  4876.1  1799.6
  4944.3 1799.97  4958.8 1799.43  4978.3 1797.04  4983.5 1797.83  4989.5 1794.72
    4990 1794.22  5010.8 1794.22  5011.3 1794.72  5012.2 1795.46  5017.6 1799.92
  5019.8 1800.73  5031.5 1804.31  5041.9 1805.17  5062.7 1804.45    5091 1804.63
  5104.9 1804.23  5160.8 1804.98  5165.9  1805.8  5175.6 1806.08    5220 1805.84
#Mann= 5 ,-1 , 0
  4103.9     .05       0  4989.5     .05       0  5011.3     .05       0
  5012.2     .12       0  5019.8     .05       0
Bank Sta=4989.5,5011.3
XS Rating Curve= 0 ,0
Exp/Cntr=0.3,0.1

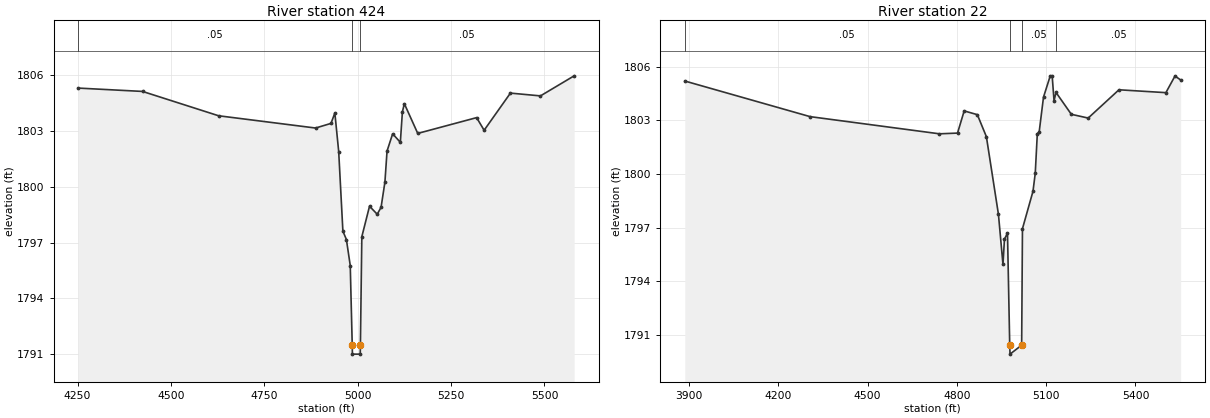
Type RM Length L Ch R = 1 ,424     ,402,402,402
BEGIN DESCRIPTION:
Mapping XS 54f5c4eb
END DESCRIPTION:
XS GIS Cut Line= 4
      1609364.38      6808520.48      1609874.79      6808757.45
      1610288.85      6808653.29      1610624.75      6808619.44
#Sta/Elev= 30
  4252.2 1805.32  4424.1 1805.14  4627.7 1803.83  4887.3 1803.17  4928.6 1803.42
  4938.9 1803.98  4949.2  1801.9  4960.4 1797.62  4969.8 1797.17  4980.1 1795.77
  4985.4  1791.5  4985.9    1791  5006.8    1791  5007.3  1791.5  5011.1 1797.32
  5031.7 1798.96  5052.3 1798.53  5062.6  1798.9  5072.9 1800.26  5078.6 1801.93
  5093.6 1802.86  5114.2  1802.4  5119.7 1804.04  5124.9 1804.48  5160.8 1802.88
  5318.4 1803.73  5338.5 1803.05  5408.9 1805.05  5489.3  1804.9  5579.5 1805.98
#Mann= 3 ,-1 , 0
  4252.2     .05       0  4985.4     .05       0  5007.3     .05       0
Bank Sta=4985.4,5007.3
XS Rating Curve= 0 ,0
Exp/Cntr=0.3,0.1

Type RM Length L Ch R = 1 ,22      ,0,0,0
BEGIN DESCRIPTION:
Elm 01 91 10406.645
END DESCRIPTION:
XS GIS Cut Line= 5
      1609333.11      6808559.53      1610109.19      6809046.69
      1610304.58      6809015.99      1610475.45      6808885.48
      1610760.08      6808705.45
#Sta/Elev= 30
  3885.9 1805.19  4306.8  1803.2  4741.5 1802.24  4802.2 1802.28  4824.6 1803.52
  4868.8 1803.31  4899.2 1802.08  4939.7 1797.74  4954.9 1794.94  4959.9 1796.35
  4970.1  1796.7  4977.6 1790.43  4978.6 1789.93  5017.7 1790.43  5020.4 1796.94
  5055.8 1799.03  5063.4 1800.04  5070.3 1802.24  5076.6 1802.35  5091.1 1804.29
  5113.8 1805.48  5120.2 1805.48  5126.5 1804.09  5133.2 1804.55  5184.6 1803.33
  5241.2 1803.12  5344.6  1804.7  5502.3 1804.54  5532.9 1805.47  5551.8 1805.25
#Mann= 4 ,-1 , 0
  3885.9     .05       0  4977.6     .07       0  5017.7     .05       0
  5133.2     .05       0
Bank Sta=4977.6,5017.7
XS Rating Curve= 0 ,0
Exp/Cntr=0.3,0.1

Chan Stop Cuts=-1
Use User Specified Reach Order=0
Composite Channel Slope=5