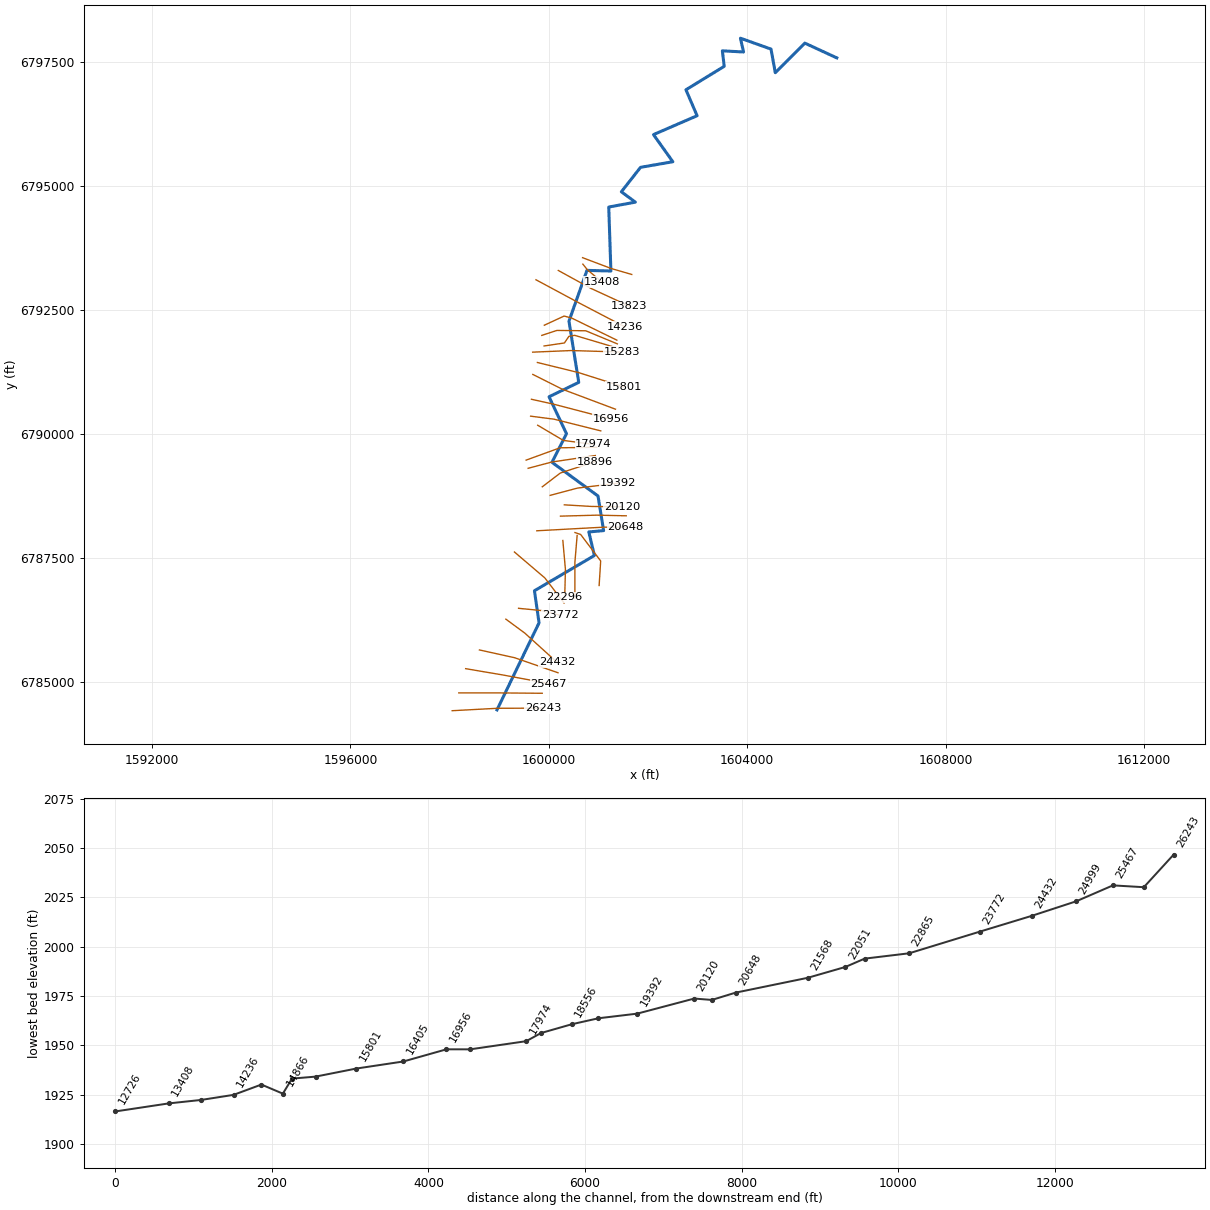
--- Elm 01 94.prj (project) ---

Proj Title=Elm 01 94 Base Level Engineering
Current Plan=p01
Default Exp/Contr=0.3,0.1
English Units
Geom File=g01
Flow File=f01
Plan File=p01
BEGIN DESCRIPTION:
Elm 01 94
END DESCRIPTION:

--- Elm 01 94.p01 (plan) ---

Plan Title=Multiple Run
Short Identifier=Multiple
Geom File=g01
Flow File=f01
Subcritical Flow
K Sum by GR= 0
Std Step Tol= 0.01
Critical Tol= 0.01
Num of Std Step Trials= 20
Max Error Tol= 0.3
Flow Tol Ratio= 0.001
Split Flow NTrial= 30
Split Flow Tol= 0.02
Split Flow Ratio= 0.02
Log Output Level= 0
Friction Slope Method= 1
Unsteady Friction Slope Method= 2
Unsteady Bridges Friction Slope Method= 1
Parabolic Critical Depth
Global Vel Dist=  1 , 1 , 1
Global Log Level= 0
CheckData=True
Encroach Param= -1, 0, 0, 0
BEGIN DESCRIPTION:
Multiple Run
END DESCRIPTION:

--- Elm 01 94.f01 (steady flow) ---

Flow Title=Multiple
Number of Profiles=7
Profile Names=10-year,25-year,50-year,1pct_min,100-year,1pct_plu,500-year
River Rch & RM= Elm 01 94,Reach-1,26243
     276     395     498     390     625     860     998
River Rch & RM= Elm 01 94,Reach-1,22865
     411     595     755     594     952    1310    1530
River Rch & RM= Elm 01 94,Reach-1,17974
     546     800    1020     808    1300    1780    2110
River Rch & RM= Elm 01 94,Reach-1,13408
     520     752     952     745    1190    1640    1910
Boundary for River Rch & Prof#=Elm 01 94,Reach-1,1
Up Type=0
Dn Type=3
Dn Slope=0.001
Boundary for River Rch & Prof#=Elm 01 94,Reach-1,2
Up Type=0
Dn Type=3
Dn Slope=0.001
Boundary for River Rch & Prof#=Elm 01 94,Reach-1,3
Up Type=0
Dn Type=3
Dn Slope=0.001
Boundary for River Rch & Prof#=Elm 01 94,Reach-1,4
Up Type=0
Dn Type=3
Dn Slope=0.001
Boundary for River Rch & Prof#=Elm 01 94,Reach-1,5
Up Type=0
Dn Type=3
Dn Slope=0.001
Boundary for River Rch & Prof#=Elm 01 94,Reach-1,6
Up Type=0
Dn Type=3
Dn Slope=0.001
Boundary for River Rch & Prof#=Elm 01 94,Reach-1,7
Up Type=0
Dn Type=3
Dn Slope=0.001

--- Elm 01 94.g01 (geometry) ---

Geom Title=Existing Conditions

River Reach=Elm 01 94,Reach-1
Reach XY= 30
      1598955.00      6784438.00      1599802.86      6786193.88
      1599709.97      6786840.59      1600918.35      6787551.36
      1600806.03      6788026.33      1601104.46      6788053.54
      1600991.50      6788751.40      1600063.84      6789431.05
      1600355.85      6790008.53      1600004.11      6790752.83
      1600603.12      6791043.69      1600406.05      6792277.57
      1600768.36      6793302.14      1601251.25      6793289.55
      1601207.84      6794579.99      1601744.58      6794678.19
      1601462.28      6794887.90      1601848.93      6795380.52
      1602500.26      6795493.62      1602109.96      6796040.61
      1602988.81      6796421.30      1602764.13      6796944.74
      1603535.79      6797417.91      1603498.48      6797730.32
      1603925.53      6797707.21      1603862.54      6797984.93
      1604479.09      6797765.46      1604565.43      6797289.03
      1605160.94      6797885.75      1605805.00      6797588.00

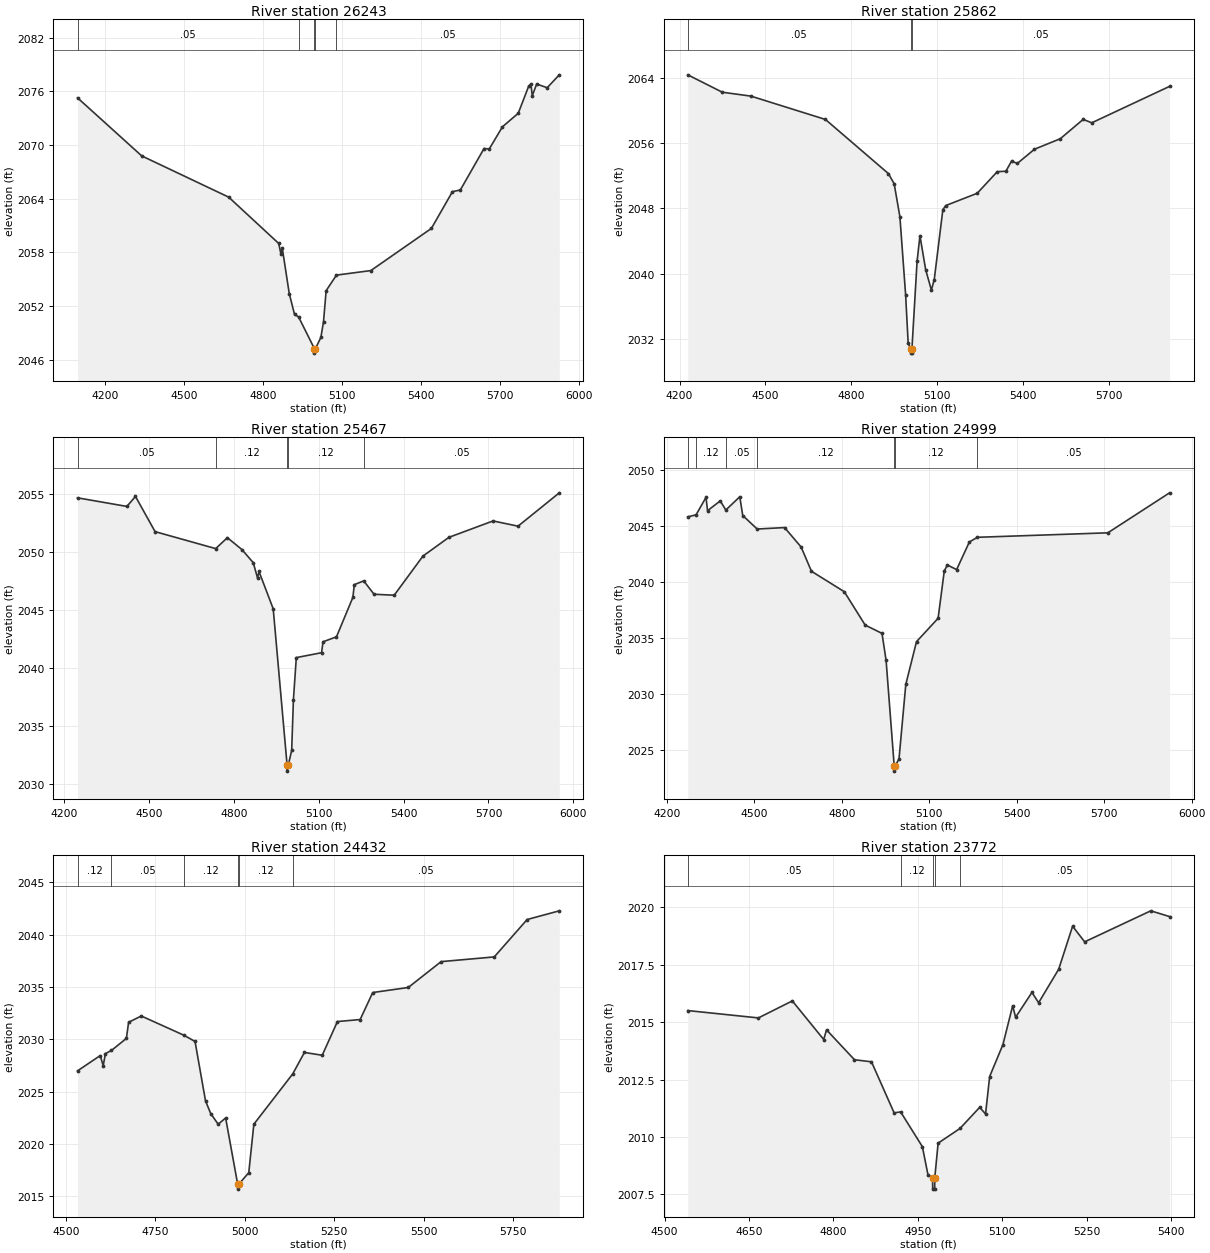
Type RM Length L Ch R = 1,26243,381,381,381
BEGIN DESCRIPTION:
Elm 01 94 25967.215
END DESCRIPTION:
XS GIS Cut Line= 3
      1598051.45      6784421.32      1598954.94      6784469.88
      1599881.14      6784473.40
#Sta/Elev= 30
  4095.2 2075.29  4339.1 2068.80  4669.6 2064.19  4859.9 2059.01  4868.3 2057.83
  4873.3 2058.50  4899.9 2053.41  4919.9 2051.08  4935.3 2050.80  4995.5 2047.25
  4995.8 2046.75  4999.5 2047.25  5020.1 2048.51  5030.1 2050.26  5040.1 2053.73
  5079.3 2055.47  5210.1 2055.98  5440.1 2060.69  5520.1 2064.80  5550.1 2064.99
  5640.1 2069.62  5660.1 2069.58  5710.1 2072.05  5770.1 2073.56  5810.1 2076.61
  5818.4 2076.82  5823.4 2075.52  5840.1 2076.83  5880.1 2076.42  5926.2 2077.86
#Mann=5,-1,0
  4095.2    0.05       0  4935.3    0.12       0  4995.5    0.07       0
  4999.5    0.12       0  5079.3    0.05       0
Bank Sta=4995.5,4999.5
Exp/Cntr=0.3,0.1

Type RM Length L Ch R = 1,25862,395,395,395
BEGIN DESCRIPTION:
Elm 01 94 25862.39
END DESCRIPTION:
XS GIS Cut Line= 3
      1598184.30      6784780.69      1598957.73      6784780.69
      1599866.57      6784772.88
#Sta/Elev= 30
  4228.8 2064.44  4349.5 2062.30  4449.5 2061.82  4709.5 2058.95  4929.5 2052.29
  4949.5 2051.04  4969.5 2046.99  4989.5 2037.39  4998.4 2031.44  5007.5 2030.71
  5007.7 2030.21  5011.2 2030.21  5011.5 2030.71  5029.5 2041.50  5039.5 2044.65
  5059.5 2040.48  5079.5 2037.96  5089.5 2039.26  5119.5 2047.85  5129.5 2048.36
  5239.5 2049.87  5309.5 2052.53  5339.5 2052.58  5359.5 2053.83  5379.5 2053.54
  5439.5 2055.29  5529.5 2056.58  5609.5 2058.96  5639.5 2058.54  5911.1 2063.02
#Mann=3,-1,0
  4228.8    0.05       0  5007.5    0.05       0  5011.5    0.05       0
Bank Sta=5007.5,5011.5
Exp/Cntr=0.3,0.1

Type RM Length L Ch R = 1,25467,468,468,468
BEGIN DESCRIPTION:
Elm 01 94 25466.6
END DESCRIPTION:
XS GIS Cut Line= 3
      1598323.08      6785269.36      1599065.23      6785143.50
      1599998.37      6784969.90
#Sta/Elev= 30
  4248.3 2054.65  4422.7 2053.91  4453.1 2054.77  4522.3 2051.74  4736.4 2050.28
  4777.7 2051.22  4829.0 2050.20  4869.0 2049.07  4884.3 2047.75  4889.4 2048.31
  4939.6 2045.10  4988.7 2031.63  4988.9 2031.13  4992.7 2031.63  5004.8 2032.91
  5011.0 2037.29  5021.2 2040.90  5110.4 2041.32  5115.5 2042.26  5163.1 2042.69
  5221.0 2046.08  5226.1 2047.18  5259.3 2047.50  5295.8 2046.35  5367.0 2046.27
  5468.7 2049.64  5560.3 2051.25  5716.2 2052.66  5804.4 2052.21  5950.2 2055.08
#Mann=5,-1,0
  4248.3    0.05       0  4736.4    0.12       0  4988.7    0.07       0
  4992.7    0.12       0  5259.3    0.05       0
Bank Sta=4988.7,4992.7
Exp/Cntr=0.3,0.1

Type RM Length L Ch R = 1,24999,567,567,567
BEGIN DESCRIPTION:
Elm 01 94 24998.58
END DESCRIPTION:
XS GIS Cut Line= 3
      1598600.82      6785646.97      1599308.28      6785490.73
      1600185.02      6785186.90
#Sta/Elev= 30
  4271.8 2045.83  4300.3 2046.01  4334.5 2047.58  4339.6 2046.38  4383.3 2047.26
  4402.3 2046.44  4450.2 2047.63  4460.4 2045.95  4509.8 2044.74  4603.8 2044.87
  4660.6 2043.13  4696.0 2040.96  4808.6 2039.13  4880.3 2036.14  4938.0 2035.40
  4952.0 2032.99  4979.7 2023.57  4979.9 2023.07  4983.7 2023.57  4996.3 2024.16
  5019.6 2030.83  5056.3 2034.66  5130.4 2036.75  5151.6 2040.99  5162.2 2041.52
  5193.9 2041.11  5237.6 2043.58  5265.0 2044.00  5712.5 2044.40  5924.2 2047.98
#Mann=7,-1,0
  4271.8    0.05       0  4300.3    0.12       0  4402.3    0.05       0
  4509.8    0.12       0  4979.7    0.07       0  4983.7    0.12       0
  5265.0    0.05       0
Bank Sta=4979.7,4983.7
Exp/Cntr=0.3,0.1

Type RM Length L Ch R = 1,24432,660,660,660
BEGIN DESCRIPTION:
Elm 01 94 24432.12
END DESCRIPTION:
XS GIS Cut Line= 3
      1599134.69      6786267.62      1599516.62      6785985.52
      1600163.33      6785399.56
#Sta/Elev= 30
  4532.1 2026.99  4595.6 2028.45  4604.0 2027.49  4610.2 2028.64  4627.1 2028.94
  4668.8 2030.09  4675.0 2031.63  4710.5 2032.23  4829.2 2030.40  4860.8 2029.80
  4890.1 2024.13  4904.7 2022.91  4925.5 2021.90  4946.4 2022.49  4979.9 2016.20
  4980.1 2015.70  4983.9 2016.20  5011.1 2017.27  5025.3 2021.90  5134.2 2026.71
  5166.7 2028.75  5216.5 2028.48  5259.1 2031.70  5322.6 2031.89  5357.8 2034.47
  5457.1 2034.95  5549.0 2037.42  5697.7 2037.87  5789.6 2041.44  5879.6 2042.27
#Mann=6,-1,0
  4532.1    0.12       0  4627.1    0.05       0  4829.2    0.12       0
  4979.9    0.07       0  4983.9    0.12       0  5134.2    0.05       0
Bank Sta=4979.9,4983.9
Exp/Cntr=0.3,0.1

Type RM Length L Ch R = 1,23772,907,907,907
BEGIN DESCRIPTION:
Elm 01 94 23772.41
END DESCRIPTION:
XS GIS Cut Line= 3
      1599390.06      6786486.56      1599851.86      6786441.42
      1600231.94      6786344.67
#Sta/Elev= 30
  4541.3 2015.50  4666.8 2015.18  4727.1 2015.92  4782.9 2014.24  4787.9 2014.66
  4837.6 2013.36  4867.8 2013.27  4908.0 2011.05  4919.6 2011.09  4958.2 2009.58
  4968.3 2008.34  4976.3 2008.23  4976.6 2007.73  4980.1 2007.73  4980.3 2008.23
  4986.2 2009.73  5025.1 2010.37  5060.1 2011.29  5070.5 2011.00  5077.8 2012.63
  5101.4 2014.02  5118.7 2015.71  5123.9 2015.21  5153.0 2016.29  5164.8 2015.84
  5200.5 2017.30  5225.2 2019.17  5246.6 2018.49  5364.1 2019.84  5397.5 2019.59
#Mann=5,-1,0
  4541.3    0.05       0  4919.6    0.12       0  4976.3    0.07       0
  4980.3    0.12       0  5025.1    0.05       0
Bank Sta=4976.3,4980.3
Exp/Cntr=0.3,0.1

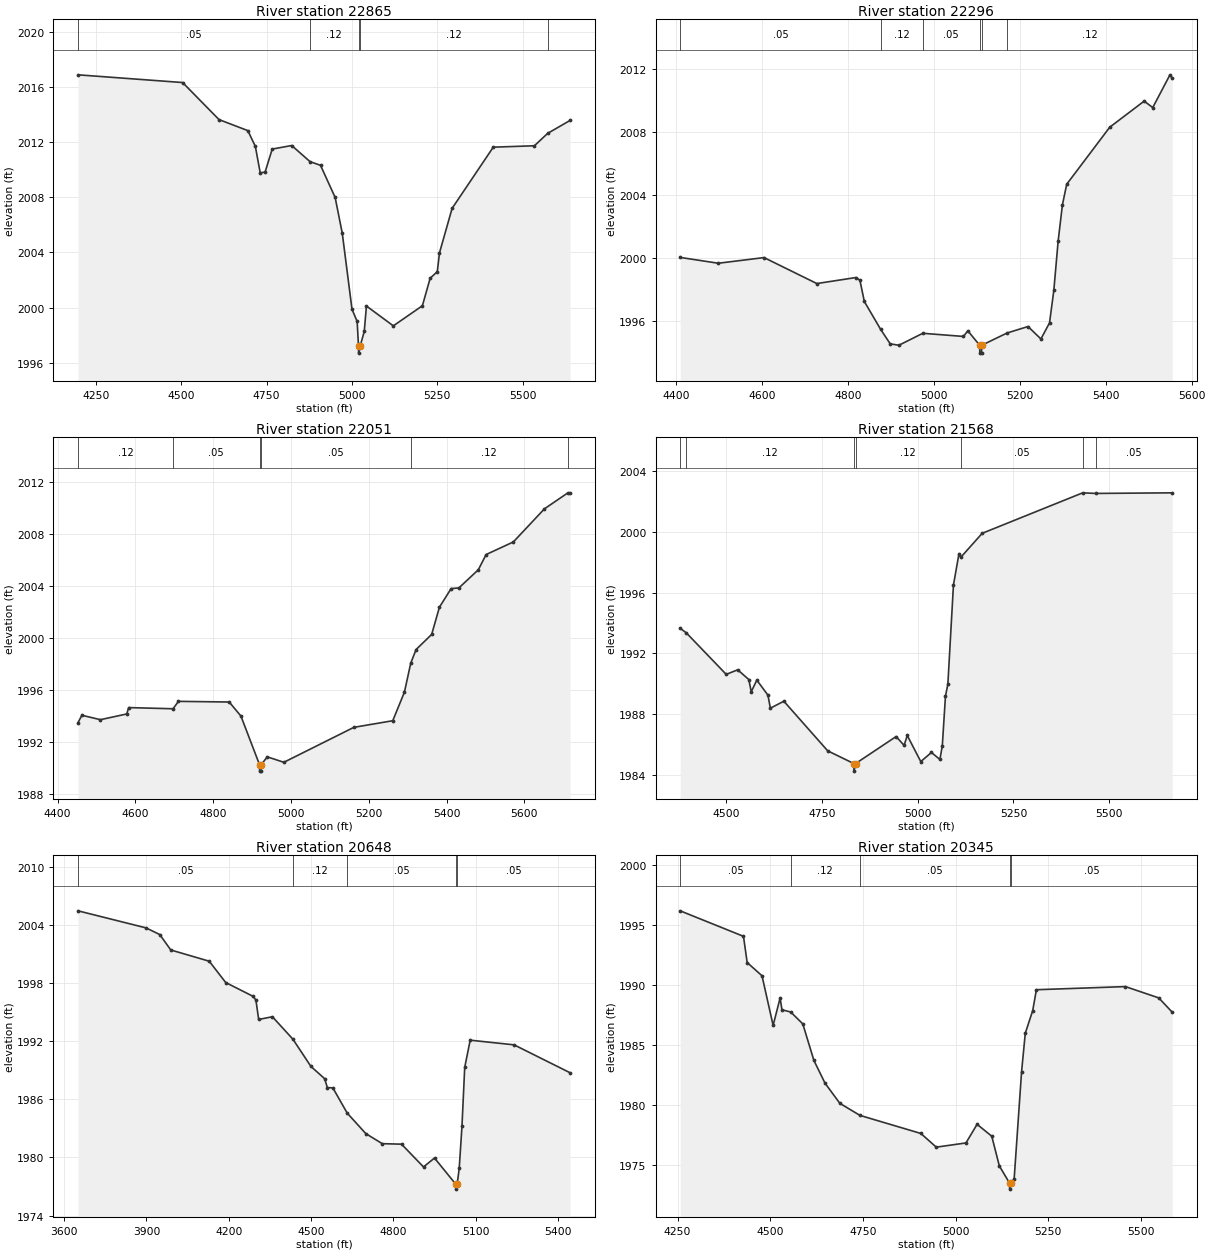
Type RM Length L Ch R = 1,22865,569,569,569
BEGIN DESCRIPTION:
Elm 01 94 22865.13
END DESCRIPTION:
XS GIS Cut Line= 3
      1599306.69      6787622.00      1599921.30      6787097.67
      1600306.69      6786594.23
#Sta/Elev= 30
  4197.3 2016.89  4503.9 2016.33  4610.5 2013.64  4695.0 2012.84  4717.0 2011.69
  4731.2 2009.78  4745.5 2009.83  4766.4 2011.50  4823.5 2011.76  4877.2 2010.59
  4908.0 2010.32  4950.8 2007.99  4971.7 2005.39  5000.2 1999.87  5015.3 1998.99
  5019.3 1997.19  5019.6 1996.69  5023.9 1997.19  5036.1 1998.26  5042.5 2000.11
  5121.3 1998.67  5206.5 2000.13  5229.3 2002.13  5250.1 2002.60  5256.6 2003.97
  5293.6 2007.20  5414.2 2011.64  5534.7 2011.74  5573.6 2012.64  5639.2 2013.58
#Mann=5,-1,0
  4197.3    0.05       0  4877.2    0.12       0  5019.3    0.07       0
  5023.9    0.12       0  5573.6    0.05       0
Bank Sta=5019.3,5023.9
Exp/Cntr=0.3,0.1

Type RM Length L Ch R = 1,22296,245,245,245
BEGIN DESCRIPTION:
Elm 01 94 22295.62
END DESCRIPTION:
XS GIS Cut Line= 3
      1600282.42      6787854.58      1600334.50      6787271.28
      1600320.62      6786712.67
#Sta/Elev= 30
  4410.4 2000.06  4499.0 1999.69  4605.4 2000.05  4728.2 1998.40  4818.6 1998.78
  4828.3 1998.62  4838.7 1997.26  4876.6 1995.49  4898.9 1994.57  4919.0 1994.48
  4974.7 1995.24  5069.3 1995.04  5079.3 1995.40  5107.0 1994.48  5107.3 1993.98
  5111.3 1993.98  5111.7 1994.48  5170.8 1995.26  5219.4 1995.67  5249.4 1994.88
  5269.4 1995.90  5279.4 1997.96  5289.4 2001.08  5299.4 2003.40  5309.4 2004.71
  5409.4 2008.33  5489.5 2009.99  5509.5 2009.58  5549.5 2011.66  5554.8 2011.45
#Mann=6,-1,0
  4410.4    0.05       0  4876.6    0.12       0  4974.7    0.05       0
  5107.0    0.05       0  5111.7    0.05       0  5170.8    0.12       0
Bank Sta=5107,5111.7
Exp/Cntr=0.3,0.1

Type RM Length L Ch R = 1,22051,483,483,483
BEGIN DESCRIPTION:
Elm 01 94 22050.56
END DESCRIPTION:
XS GIS Cut Line= 3
      1600570.61      6787955.36      1600525.47      6787413.64
      1600525.47      6786692.23
#Sta/Elev= 30
  4452.3 1993.49  4462.2 1994.06  4509.9 1993.72  4577.6 1994.16  4582.6 1994.65
  4696.6 1994.56  4710.5 1995.13  4841.0 1995.08  4871.1 1994.00  4918.9 1990.26
  4919.3 1989.76  4923.3 1989.76  4923.6 1990.26  4938.8 1990.86  4981.5 1990.44
  5161.5 1993.13  5261.5 1993.64  5291.5 1995.84  5307.7 1998.07  5321.5 1999.12
  5361.5 2000.28  5381.5 2002.38  5411.5 2003.81  5431.5 2003.86  5481.5 2005.26
  5501.5 2006.43  5571.5 2007.40  5651.5 2009.95  5711.8 2011.18  5717.3 2011.18
#Mann=6,-1,0
  4452.3    0.12       0  4696.6    0.05       0  4918.9    0.03       0
  4923.6    0.05       0  5307.7    0.12       0  5711.8    0.05       0
Bank Sta=4918.9,4923.6
Exp/Cntr=0.3,0.1

Type RM Length L Ch R = 1,21568,920,920,920
BEGIN DESCRIPTION:
Mapping XS 7ae02c40
END DESCRIPTION:
XS GIS Cut Line= 4
      1600526.98      6788014.37      1600641.61      6787975.29
      1601045.26      6787441.44      1601014.01      6786946.61
#Sta/Elev= 30
  4379.0 1993.66  4394.9 1993.36  4499.3 1990.62  4529.3 1990.92  4558.4 1990.28
  4564.7 1989.47  4579.3 1990.24  4608.4 1989.25  4614.7 1988.39  4650.0 1988.85
  4764.5 1985.58  4832.9 1984.74  4833.3 1984.24  4837.6 1984.74  4943.4 1986.52
  4964.3 1985.94  4972.6 1986.59  5007.9 1984.87  5035.8 1985.47  5057.9 1985.01
  5064.2 1985.91  5072.4 1989.18  5078.7 1989.97  5093.3 1996.51  5107.8 1998.58
  5112.6 1998.34  5168.4 1999.92  5431.2 2002.59  5465.4 2002.55  5665.2 2002.59
#Mann=7,-1,0
  4379.0    0.05       0  4394.9    0.12       0  4832.9    0.07       0
  4837.6    0.12       0  5112.6    0.05       0  5431.2    0.12       0
  5465.4    0.05       0
Bank Sta=4832.9,4837.6
Exp/Cntr=0.3,0.1

Type RM Length L Ch R = 1,20648,303,303,303
BEGIN DESCRIPTION:
Elm 01 94 20647.5
END DESCRIPTION:
XS GIS Cut Line= 3
      1599757.43      6788050.22      1601101.16      6788123.13
      1601549.05      6788123.13
#Sta/Elev= 30
  3650.5 2005.45  3898.4 2003.69  3948.5 2003.00  3988.6 2001.41  4128.8 2000.25
  4188.9 1998.05  4289.0 1996.62  4299.0 1996.24  4309.0 1994.24  4359.1 1994.52
  4433.9 1992.20  4499.3 1989.40  4549.4 1988.13  4559.4 1987.21  4579.4 1987.18
  4631.9 1984.57  4699.6 1982.46  4759.7 1981.42  4829.8 1981.37  4909.9 1979.02
  4950.0 1979.94  5027.7 1977.23  5028.0 1976.73  5032.5 1977.23  5040.1 1978.87
  5050.1 1983.21  5060.1 1989.29  5080.1 1992.10  5240.1 1991.62  5444.1 1988.74
#Mann=5,-1,0
  3650.5    0.05       0  4433.9    0.12       0  4631.9    0.05       0
  5027.7    0.05       0  5032.5    0.05       0
Bank Sta=5027.7,5032.5
Exp/Cntr=0.3,0.1

Type RM Length L Ch R = 1,20345,225,225,225
BEGIN DESCRIPTION:
Elm 01 94 20344.92
END DESCRIPTION:
XS GIS Cut Line= 3
      1600234.39      6788345.79      1600974.43      6788365.32
      1601561.29      6788352.33
#Sta/Elev= 30
  4257.0 1996.17  4427.7 1994.05  4437.7 1991.87  4477.7 1990.77  4507.7 1986.64
  4526.5 1988.92  4531.5 1987.94  4555.1 1987.76  4587.7 1986.77  4617.7 1983.73
  4647.7 1981.84  4687.8 1980.16  4742.0 1979.16  4906.1 1977.66  4947.8 1976.52
  5027.9 1976.87  5057.9 1978.42  5097.5 1977.43  5117.9 1974.96  5145.5 1973.53
  5145.9 1973.03  5150.3 1973.53  5157.9 1973.88  5177.9 1982.79  5187.9 1985.99
  5207.9 1987.87  5217.9 1989.61  5458.0 1989.87  5548.0 1988.93  5584.3 1987.74
#Mann=5,-1,0
  4257.0    0.05       0  4555.1    0.12       0  4742.0    0.05       0
  5145.5    0.05       0  5150.3    0.05       0
Bank Sta=5145.5,5150.3
Exp/Cntr=0.3,0.1

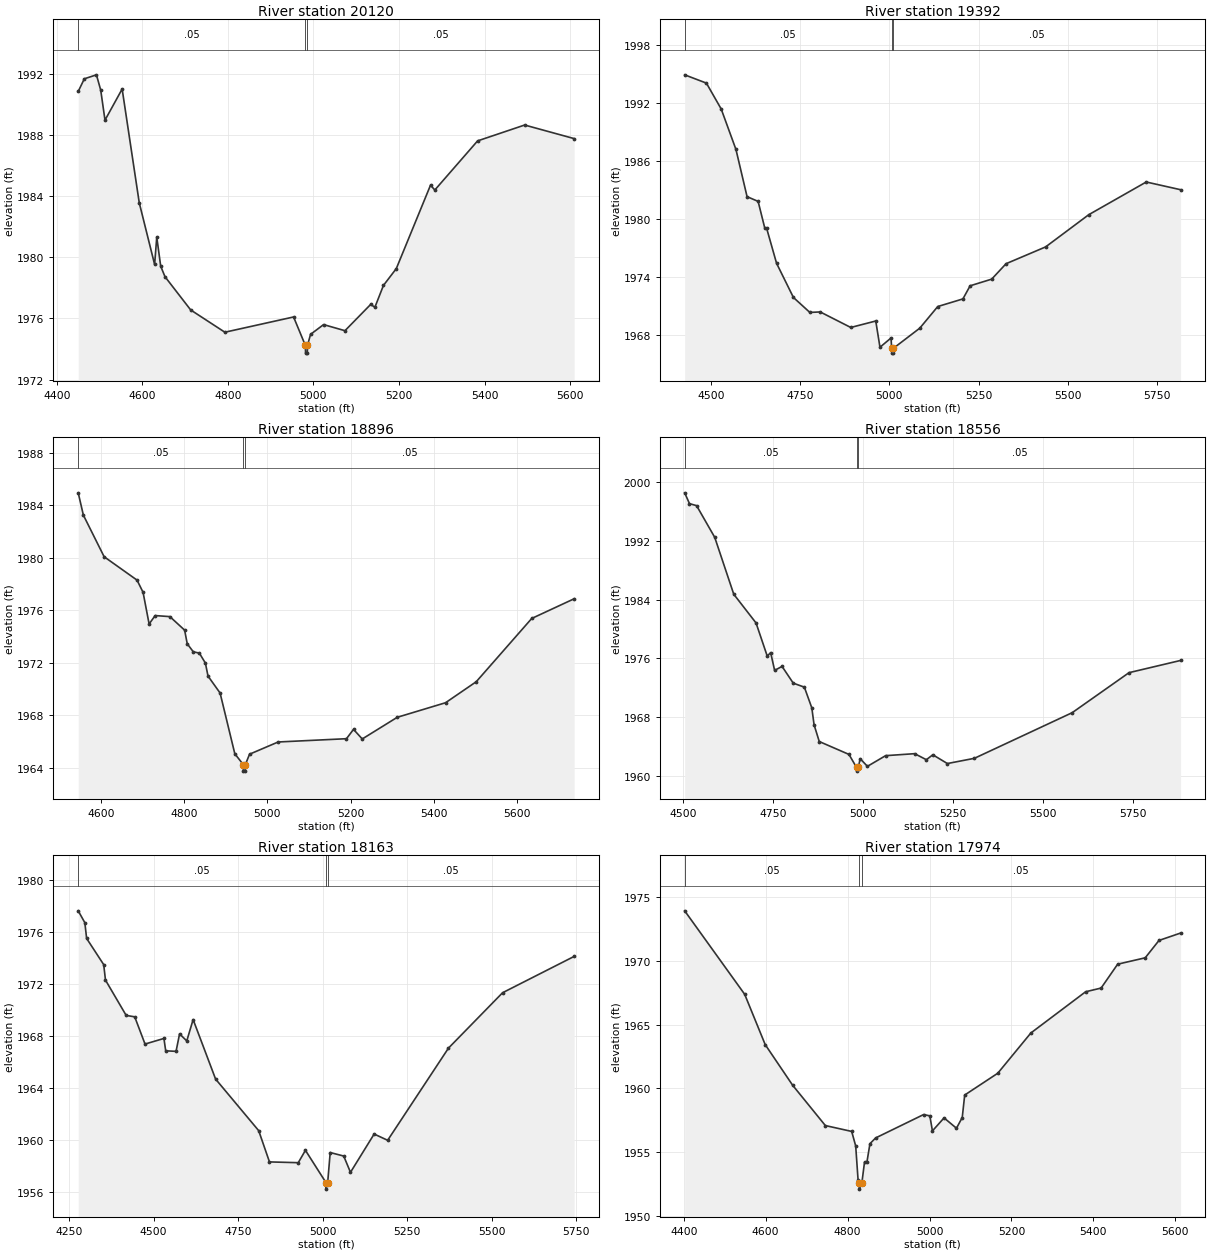
Type RM Length L Ch R = 1,20120,728,728,728
BEGIN DESCRIPTION:
Elm 01 94 20119.55
END DESCRIPTION:
XS GIS Cut Line= 3
      1600312.52      6788573.65      1600859.41      6788541.10
      1601470.72      6788534.60
#Sta/Elev= 30
  4450.3 1990.88  4464.6 1991.71  4492.9 1991.97  4502.9 1990.97  4512.9 1989.00
  4553.0 1991.04  4593.0 1983.58  4628.9 1979.54  4633.9 1981.33  4643.1 1979.43
  4653.1 1978.74  4713.2 1976.56  4793.1 1975.10  4953.7 1976.10  4981.3 1974.23
  4981.7 1973.73  4985.8 1973.73  4986.1 1974.23  4993.4 1974.96  5023.8 1975.60
  5073.8 1975.20  5133.8 1976.92  5143.8 1976.74  5163.8 1978.17  5193.8 1979.27
  5273.8 1984.74  5283.8 1984.42  5383.8 1987.64  5493.8 1988.68  5609.5 1987.79
#Mann=3,-1,0
  4450.3    0.05       0  4981.3    0.05       0  4986.1    0.05       0
Bank Sta=4981.3,4986.1
Exp/Cntr=0.3,0.1

Type RM Length L Ch R = 1,19392,496,496,496
BEGIN DESCRIPTION:
Elm 01 94 19391.68
END DESCRIPTION:
XS GIS Cut Line= 3
      1600026.10      6788764.63      1600581.63      6788912.20
      1601390.57      6789009.79
#Sta/Elev= 30
  4426.4 1994.93  4487.3 1994.07  4528.7 1991.39  4570.1 1987.19  4601.2 1982.30
  4632.2 1981.81  4650.7 1979.06  4655.9 1979.04  4683.9 1975.39  4731.1 1971.85
  4777.1 1970.30  4806.2 1970.35  4891.8 1968.74  4961.8 1969.41  4973.6 1966.69
  5004.6 1967.65  5006.4 1966.58  5006.7 1966.08  5010.8 1966.08  5011.2 1966.58
  5085.2 1968.67  5135.5 1970.91  5206.0 1971.70  5226.2 1973.06  5286.6 1973.75
  5326.9 1975.35  5437.7 1977.09  5558.6 1980.43  5719.7 1983.82  5816.0 1983.02
#Mann=3,-1,0
  4426.4    0.05       0  5006.4    0.05       0  5011.2    0.05       0
Bank Sta=5006.4,5011.2
Exp/Cntr=0.3,0.1

Type RM Length L Ch R = 1,18896,340,340,340
BEGIN DESCRIPTION:
Elm 01 94 18896.2
END DESCRIPTION:
XS GIS Cut Line= 3
      1599867.65      6788937.36      1600232.24      6789215.15
      1600928.44      6789444.32
#Sta/Elev= 30
  4545.7 1984.93  4558.1 1983.23  4608.0 1980.06  4687.0 1978.28  4701.5 1977.35
  4716.0 1974.94  4730.6 1975.58  4765.9 1975.50  4801.3 1974.47  4807.6 1973.43
  4822.1 1972.82  4836.7 1972.72  4851.2 1971.96  4857.5 1970.97  4886.5 1969.68
  4921.9 1965.05  4942.2 1964.23  4942.6 1963.73  4946.8 1963.73  4947.2 1964.23
  4957.3 1965.02  5026.0 1965.95  5190.1 1966.20  5207.0 1966.91  5228.0 1966.18
  5312.0 1967.83  5428.1 1968.94  5501.8 1970.54  5635.1 1975.36  5737.0 1976.86
#Mann=3,-1,0
  4545.7    0.05       0  4942.2    0.05       0  4947.2    0.05       0
Bank Sta=4942.2,4947.2
Exp/Cntr=0.3,0.1

Type RM Length L Ch R = 1,18556,393,393,393
BEGIN DESCRIPTION:
Elm 01 94 18555.65
END DESCRIPTION:
XS GIS Cut Line= 3
      1599582.98      6789310.64      1600062.10      6789437.37
      1600937.07      6789567.57
#Sta/Elev= 30
  4503.5 1998.49  4516.9 1997.02  4536.6 1996.75  4587.1 1992.45  4640.1 1984.72
  4702.1 1980.82  4733.2 1976.33  4742.8 1976.79  4753.8 1974.38  4774.5 1974.92
  4805.6 1972.65  4836.6 1972.10  4857.3 1969.29  4863.6 1967.00  4878.0 1964.72
  4960.7 1962.97  4981.8 1961.20  4982.1 1960.70  4986.8 1961.20  4991.8 1962.39
  5012.1 1961.35  5062.7 1962.80  5143.6 1963.07  5176.1 1962.25  5194.1 1962.92
  5234.6 1961.73  5309.8 1962.44  5582.1 1968.64  5740.1 1974.07  5883.7 1975.73
#Mann=3,-1,0
  4503.5    0.05       0  4981.8    0.05       0  4986.8    0.05       0
Bank Sta=4981.8,4986.8
Exp/Cntr=0.3,0.1

Type RM Length L Ch R = 1,18163,189,189,189
BEGIN DESCRIPTION:
Elm 01 94 18163.42
END DESCRIPTION:
XS GIS Cut Line= 3
      1599543.19      6789475.74      1600225.47      6789724.00
      1600966.75      6789734.42
#Sta/Elev= 30
  4277.0 1977.61  4296.6 1976.70  4301.9 1975.49  4352.4 1973.48  4357.7 1972.29
  4418.9 1969.58  4444.2 1969.47  4474.7 1967.38  4530.6 1967.81  4535.9 1966.86
  4566.5 1966.82  4576.9 1968.16  4598.2 1967.62  4617.0 1969.26  4683.5 1964.69
  4811.0 1960.73  4842.9 1958.33  4928.1 1958.27  4949.3 1959.22  5010.1 1956.74
  5010.4 1956.24  5015.1 1956.74  5022.6 1959.05  5062.6 1958.78  5082.6 1957.53
  5152.6 1960.47  5192.6 1959.99  5372.6 1967.07  5532.6 1971.32  5744.4 1974.11
#Mann=3,-1,0
  4277.0    0.05       0  5010.1    0.05       0  5015.1    0.05       0
Bank Sta=5010.1,5015.1
Exp/Cntr=0.3,0.1

Type RM Length L Ch R = 1,17974,717,717,717
BEGIN DESCRIPTION:
Elm 01 94 17973.94
END DESCRIPTION:
XS GIS Cut Line= 3
      1599775.85      6790178.84      1600291.44      6789873.31
      1600897.35      6789791.71
#Sta/Elev= 30
  4402.3 1973.91  4548.8 1967.37  4598.9 1963.43  4665.8 1960.25  4745.7 1957.09
  4810.0 1956.63  4819.8 1955.49  4825.6 1952.83  4828.1 1952.61  4828.6 1952.11
  4834.9 1952.61  4841.3 1954.22  4847.1 1954.21  4854.6 1955.67  4868.5 1956.12
  4985.5 1957.95  5000.8 1957.85  5007.1 1956.67  5035.5 1957.69  5065.8 1956.88
  5079.9 1957.72  5085.9 1959.48  5166.7 1961.19  5247.4 1964.34  5381.1 1967.57
  5418.9 1967.86  5459.3 1969.73  5526.6 1970.23  5560.2 1971.59  5613.0 1972.17
#Mann=3,-1,0
  4402.3    0.05       0  4828.1    0.03       0  4834.9    0.05       0
Bank Sta=4828.1,4834.9
Exp/Cntr=0.3,0.1

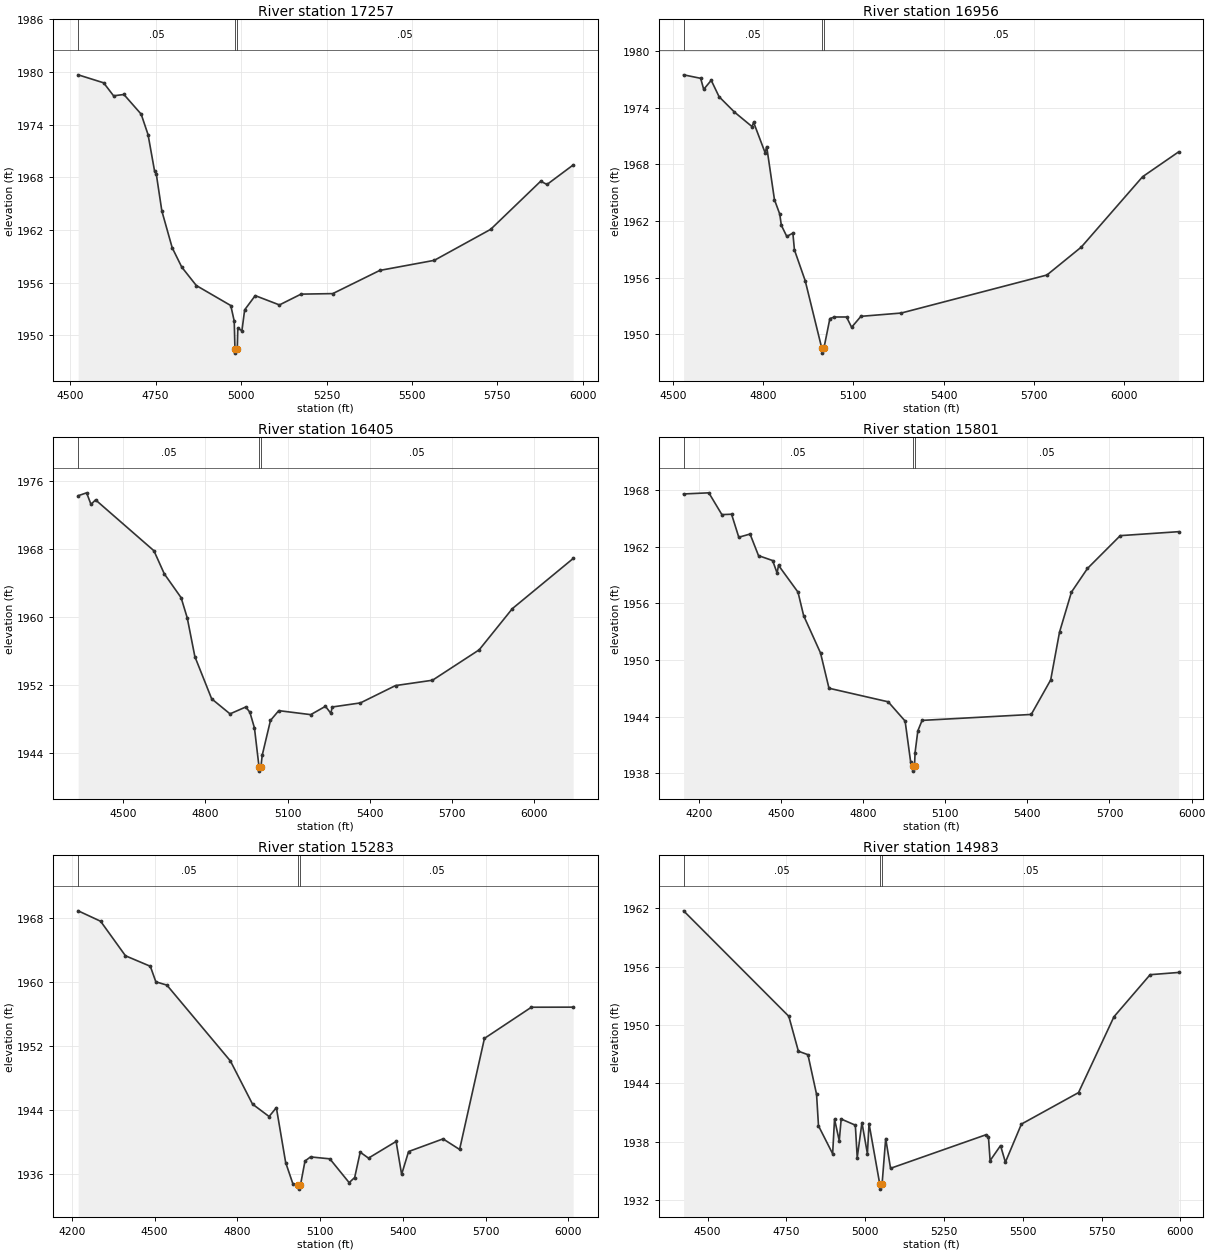
Type RM Length L Ch R = 1,17257,301,301,301
BEGIN DESCRIPTION:
Elm 01 94 17257.38
END DESCRIPTION:
XS GIS Cut Line= 3
      1599632.25      6790362.02      1600104.46      6790301.26
      1601047.13      6790065.16
#Sta/Elev= 30
  4523.6 1979.67  4598.1 1978.76  4627.2 1977.28  4657.4 1977.43  4707.9 1975.19
  4728.0 1972.86  4747.1 1968.71  4752.1 1968.37  4768.4 1964.16  4798.6 1959.98
  4826.6 1957.77  4869.2 1955.67  4970.0 1953.39  4980.1 1951.62  4982.2 1948.47
  4982.7 1947.97  4989.0 1948.47  4990.6 1950.81  5002.6 1950.52  5010.6 1952.90
  5041.5 1954.52  5112.3 1953.46  5175.5 1954.69  5268.3 1954.75  5405.8 1957.39
  5565.4 1958.54  5730.2 1962.07  5876.5 1967.55  5895.0 1967.18  5971.5 1969.40
#Mann=3,-1,0
  4523.6    0.05       0  4982.2    0.05       0  4989.0    0.05       0
Bank Sta=4982.2,4989
Exp/Cntr=0.3,0.1

Type RM Length L Ch R = 1,16956,551,551,551
BEGIN DESCRIPTION:
Elm 01 94 16956.43
END DESCRIPTION:
XS GIS Cut Line= 3
      1599649.56      6790702.74      1600104.46      6790602.04
      1601248.52      6790303.44
#Sta/Elev= 30
  4534.5 1977.49  4591.3 1977.12  4601.5 1975.95  4626.5 1976.91  4652.7 1975.17
  4703.9 1973.54  4762.5 1972.00  4767.6 1972.46  4806.1 1969.22  4811.2 1969.88
  4837.1 1964.25  4854.8 1962.72  4859.9 1961.55  4878.1 1960.36  4898.4 1960.71
  4903.6 1958.93  4939.5 1955.66  4994.8 1948.49  4995.3 1947.99  5001.6 1948.49
  5021.6 1951.65  5036.7 1951.82  5077.1 1951.82  5094.0 1950.73  5125.0 1951.89
  5259.3 1952.24  5744.4 1956.27  5858.8 1959.23  6063.0 1966.69  6182.8 1969.32
#Mann=3,-1,0
  4534.5    0.05       0  4994.8    0.05       0  5001.6    0.05       0
Bank Sta=4994.8,5001.6
Exp/Cntr=0.3,0.1

Type RM Length L Ch R = 1,16405,604,604,604
BEGIN DESCRIPTION:
Elm 01 94 16404.75
END DESCRIPTION:
XS GIS Cut Line= 3
      1599677.39      6791203.60      1600272.87      6790904.99
      1601342.97      6790502.62
#Sta/Elev= 30
  4334.6 1974.23  4365.5 1974.57  4381.4 1973.21  4398.2 1973.74  4611.6 1967.75
  4649.5 1965.03  4710.9 1962.23  4733.3 1959.85  4761.2 1955.29  4822.6 1950.32
  4889.7 1948.55  4947.2 1949.36  4962.3 1948.74  4979.0 1946.89  4995.7 1942.31
  4996.2 1941.81  5002.6 1942.31  5007.4 1943.68  5037.6 1947.78  5067.9 1948.93
  5184.7 1948.46  5238.6 1949.44  5258.1 1948.62  5263.4 1949.36  5366.3 1949.84
  5494.6 1951.88  5629.8 1952.51  5800.5 1956.09  5921.8 1960.94  6144.0 1966.84
#Mann=3,-1,0
  4334.6    0.05       0  4995.7    0.05       0  5002.6    0.05       0
Bank Sta=4995.7,5002.6
Exp/Cntr=0.3,0.1

Type RM Length L Ch R = 1,15801,518,518,518
BEGIN DESCRIPTION:
Elm 01 94 15800.68
END DESCRIPTION:
XS GIS Cut Line= 3
      1599769.17      6791444.64      1600600.38      6791240.64
      1601508.08      6790952.52
#Sta/Elev= 30
  4144.2 1967.60  4236.4 1967.72  4284.1 1965.41  4319.5 1965.45  4345.8 1963.01
  4387.0 1963.35  4417.9 1961.06  4469.4 1960.54  4485.8 1959.21  4490.9 1960.03
  4562.1 1957.19  4582.7 1954.70  4644.4 1950.74  4675.3 1947.00  4891.6 1945.56
  4953.4 1943.52  4973.9 1939.13  4980.7 1938.71  4981.2 1938.21  4987.7 1938.71
  4989.8 1940.18  4999.9 1942.48  5015.4 1943.59  5414.1 1944.22  5485.2 1947.88
  5517.4 1952.94  5561.0 1957.19  5619.5 1959.70  5739.3 1963.18  5952.4 1963.60
#Mann=3,-1,0
  4144.2    0.05       0  4980.7    0.05       0  4987.7    0.05       0
Bank Sta=4980.7,4987.7
Exp/Cntr=0.3,0.1

Type RM Length L Ch R = 1,15283,300,300,300
BEGIN DESCRIPTION:
Elm 01 94 15283.08
END DESCRIPTION:
XS GIS Cut Line= 3
      1599673.74      6791652.97      1600452.81      6791685.52
      1601466.31      6791655.13
#Sta/Elev= 30
  4223.2 1968.86  4304.5 1967.56  4394.6 1963.25  4484.7 1961.94  4504.7 1960.00
  4544.7 1959.59  4774.9 1950.12  4855.0 1944.74  4915.1 1943.19  4941.4 1944.30
  4975.1 1937.45  5001.5 1934.77  5021.6 1934.63  5022.1 1934.13  5028.7 1934.63
  5045.2 1937.64  5065.2 1938.15  5135.2 1937.91  5205.2 1934.94  5225.2 1935.58
  5245.2 1938.74  5275.3 1938.00  5375.3 1940.08  5395.3 1935.97  5420.5 1938.82
  5545.4 1940.40  5605.4 1939.08  5695.4 1952.94  5865.5 1956.83  6016.9 1956.84
#Mann=3,-1,0
  4223.2    0.05       0  5021.6    0.05       0  5028.7    0.05       0
Bank Sta=5021.6,5028.7
Exp/Cntr=0.3,0.1

Type RM Length L Ch R = 1,14983,117,117,117
BEGIN DESCRIPTION:
Elm 01 94 14982.65
END DESCRIPTION:
XS GIS Cut Line= 5
      1599904.77      6791777.67      1600314.94      6791838.44
      1600403.91      6791970.82      1600521.10      6791992.52
      1601361.52      6791741.26
#Sta/Elev= 30
  4423.6 1961.76  4757.4 1950.91  4787.8 1947.32  4818.1 1946.96  4845.5 1942.88
  4851.6 1939.64  4896.5 1936.77  4902.5 1940.33  4917.5 1938.10  4923.6 1940.34
  4968.5 1939.71  4974.5 1936.37  4989.5 1939.97  5006.8 1936.77  5011.9 1939.88
  5046.1 1933.63  5046.6 1933.13  5053.3 1933.63  5064.8 1938.33  5080.2 1935.27
  5381.9 1938.71  5390.8 1938.53  5396.1 1936.06  5429.2 1937.61  5444.6 1935.90
  5495.4 1939.82  5676.6 1943.06  5789.0 1950.86  5903.8 1955.19  5994.1 1955.42
#Mann=3,-1,0
  4423.6    0.05       0  5046.1    0.05       0  5053.3    0.05       0
Bank Sta=5046.1,5053.3
Exp/Cntr=0.3,0.1

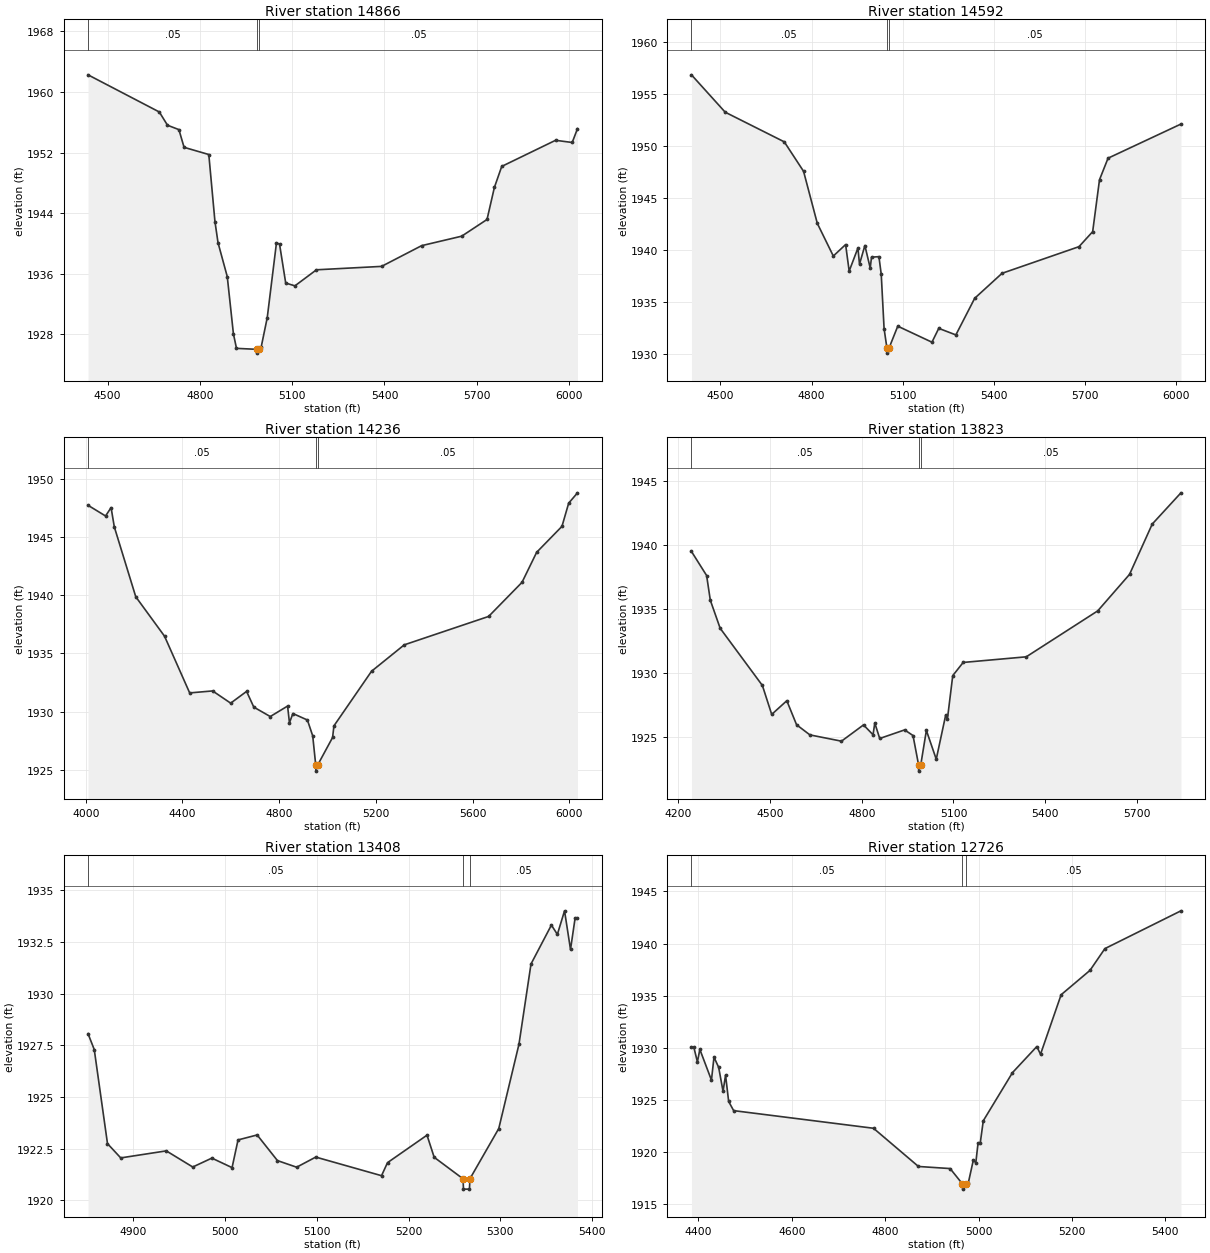
Type RM Length L Ch R = 1,14866,274,274,274
BEGIN DESCRIPTION:
Mapping XS 78220e14
END DESCRIPTION:
XS GIS Cut Line= 4
      1599858.29      6791991.10      1600162.09      6792090.92
      1600743.68      6792084.41      1601380.89      6791819.99
#Sta/Elev= 30
  4436.2 1962.27  4668.0 1957.36  4694.6 1955.61  4731.7 1955.03  4748.5 1952.69
  4828.9 1951.74  4848.9 1942.87  4858.9 1940.08  4888.9 1935.61  4908.9 1928.05
  4918.9 1926.13  4985.3 1926.00  4985.8 1925.50  4992.5 1926.00  4998.9 1926.25
  5018.9 1930.19  5048.9 1940.09  5058.9 1939.89  5078.9 1934.76  5108.9 1934.39
  5178.9 1936.51  5390.6 1936.96  5520.8 1939.70  5651.0 1940.95  5733.4 1943.16
  5757.3 1947.39  5781.2 1950.17  5956.2 1953.62  6010.3 1953.33  6027.5 1955.16
#Mann=3,-1,0
  4436.2    0.05       0  4985.3    0.05       0  4992.5    0.05       0
Bank Sta=4985.3,4992.5
Exp/Cntr=0.3,0.1

Type RM Length L Ch R = 1,14592,356,356,356
BEGIN DESCRIPTION:
Elm 01 94 14592.24
END DESCRIPTION:
XS GIS Cut Line= 4
      1599909.08      6792196.49      1600308.43      6792380.97
      1600458.17      6792341.91      1601370.91      6791895.30
#Sta/Elev= 30
  4404.8 1956.85  4515.8 1953.26  4710.3 1950.41  4773.7 1947.58  4818.9 1942.58
  4871.6 1939.44  4912.1 1940.54  4923.8 1937.99  4952.6 1940.21  4957.8 1938.66
  4975.5 1940.45  4993.1 1938.28  4997.3 1939.33  5021.7 1939.38  5029.3 1937.69
  5038.7 1932.46  5048.0 1930.61  5048.5 1930.11  5055.2 1930.61  5083.7 1932.70
  5196.2 1931.16  5218.6 1932.49  5274.9 1931.86  5336.9 1935.38  5426.9 1937.78
  5680.1 1940.34  5725.1 1941.78  5747.6 1946.77  5775.7 1948.84  6015.6 1952.12
#Mann=3,-1,0
  4404.8    0.05       0  5048.0    0.05       0  5055.2    0.05       0
Bank Sta=5048,5055.2
Exp/Cntr=0.3,0.1

Type RM Length L Ch R = 1,14236,413,413,413
BEGIN DESCRIPTION:
Elm 01 94 14235.71
END DESCRIPTION:
XS GIS Cut Line= 3
      1599741.01      6793112.76      1600613.37      6792644.03
      1601529.98      6792164.89
#Sta/Elev= 30
  4009.5 1947.72  4082.1 1946.80  4104.9 1947.52  4118.3 1945.86  4207.0 1939.86
  4326.1 1936.47  4430.0 1931.60  4524.9 1931.77  4599.6 1930.72  4665.4 1931.73
  4695.2 1930.38  4763.3 1929.57  4835.0 1930.47  4842.7 1929.03  4856.9 1929.83
  4917.0 1929.27  4938.9 1927.91  4951.5 1925.38  4952.0 1924.88  4958.8 1925.38
  5021.1 1927.77  5026.7 1928.77  5182.2 1933.46  5317.6 1935.73  5666.5 1938.17
  5804.6 1941.10  5865.2 1943.68  5969.9 1945.91  5997.6 1947.90  6034.1 1948.79
#Mann=3,-1,0
  4009.5    0.05       0  4951.5    0.05       0  4958.8    0.05       0
Bank Sta=4951.5,4958.8
Exp/Cntr=0.3,0.1

Type RM Length L Ch R = 1,13823,415,415,415
BEGIN DESCRIPTION:
Elm 01 94 13822.75
END DESCRIPTION:
XS GIS Cut Line= 3
      1600191.51      6793300.27      1600855.56      6792935.70
      1601622.17      6792582.28
#Sta/Elev= 30
  4242.6 1939.47  4292.2 1937.59  4304.3 1935.66  4336.5 1933.47  4474.7 1929.00
  4505.2 1926.74  4554.6 1927.81  4586.6 1925.93  4630.2 1925.14  4733.5 1924.65
  4805.6 1925.92  4836.8 1925.15  4842.5 1926.07  4858.6 1924.86  4940.1 1925.53
  4967.6 1925.09  4985.7 1922.81  4986.2 1922.31  4993.0 1922.81  5011.3 1925.49
  5043.6 1923.24  5074.7 1926.71  5080.2 1926.39  5097.6 1929.77  5131.7 1930.80
  5338.2 1931.24  5572.1 1934.83  5676.1 1937.68  5750.4 1941.61  5844.3 1944.05
#Mann=3,-1,0
  4242.6    0.05       0  4985.7    0.05       0  4993.0    0.05       0
Bank Sta=4985.7,4993
Exp/Cntr=0.3,0.1

Type RM Length L Ch R = 1,13408,682,682,682
BEGIN DESCRIPTION:
Elm 01 94 13407.72
END DESCRIPTION:
XS GIS Cut Line= 3
      1600686.00      6793428.55      1600779.73      6793311.39
      1601073.99      6793066.61
#Sta/Elev= 30
  4851.1 1928.07  4857.9 1927.30  4872.3 1922.75  4886.7 1922.06  4936.3 1922.40
  4965.1 1921.62  4985.9 1922.05  5007.9 1921.59  5014.4 1922.93  5035.2 1923.17
  5057.3 1921.93  5078.2 1921.61  5099.0 1922.10  5170.6 1921.20  5177.1 1921.83
  5220.1 1923.16  5227.9 1922.09  5259.3 1921.05  5259.8 1920.55  5266.3 1920.55
  5266.8 1921.05  5298.2 1923.48  5320.2 1927.56  5333.3 1931.44  5355.5 1933.32
  5362.0 1932.87  5369.8 1934.01  5376.3 1932.14  5381.3 1933.66  5383.9 1933.66
#Mann=3,-1,0
  4851.1    0.05       0  5259.3    0.05       0  5266.8    0.05       0
Bank Sta=5259.3,5266.8
Exp/Cntr=0.3,0.1

Type RM Length L Ch R = 1,12726,260,260,260
BEGIN DESCRIPTION:
Elm 01 94 12725.6
END DESCRIPTION:
XS GIS Cut Line= 3
      1600680.52      6793558.37      1601258.68      6793339.60
      1601671.39      6793220.20
#Sta/Elev= 30
  4385.4 1930.06  4390.5 1930.06  4398.1 1928.66  4403.4 1929.85  4428.2 1926.91
  4433.6 1929.11  4443.6 1928.14  4453.0 1925.84  4458.4 1927.39  4465.0 1924.87
  4475.7 1923.99  4775.1 1922.30  4871.3 1918.64  4939.1 1918.44  4965.5 1916.97
  4966.0 1916.47  4973.1 1916.97  4978.2 1917.10  4988.8 1919.25  4994.1 1919.00
  4998.9 1920.89  5003.6 1920.89  5010.1 1923.02  5072.6 1927.63  5124.7 1930.13
  5132.6 1929.39  5176.7 1935.09  5238.6 1937.43  5270.4 1939.51  5433.2 1943.13
#Mann=3,-1,0
  4385.4    0.05       0  4965.5    0.03       0  4973.1    0.05       0
Bank Sta=4965.5,4973.1
Exp/Cntr=0.3,0.1