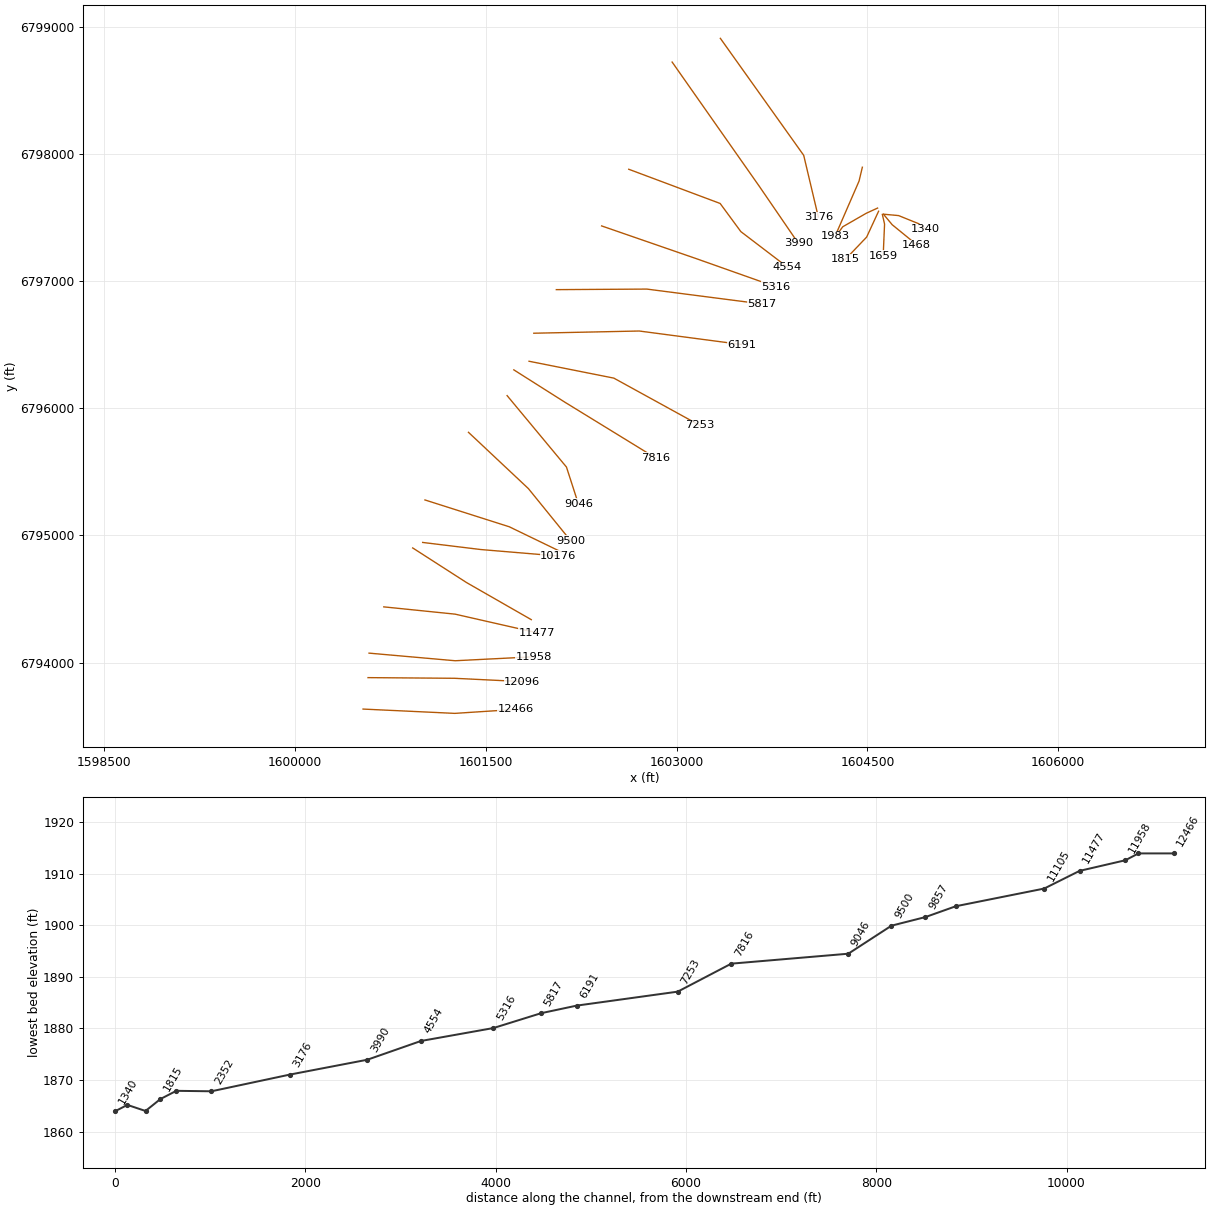
HEC-RAS study Elm 01 94.prj: Elm 01 94 Base Level Engineering

--- Elm 01 94.g01 (geometry) --- (continued)

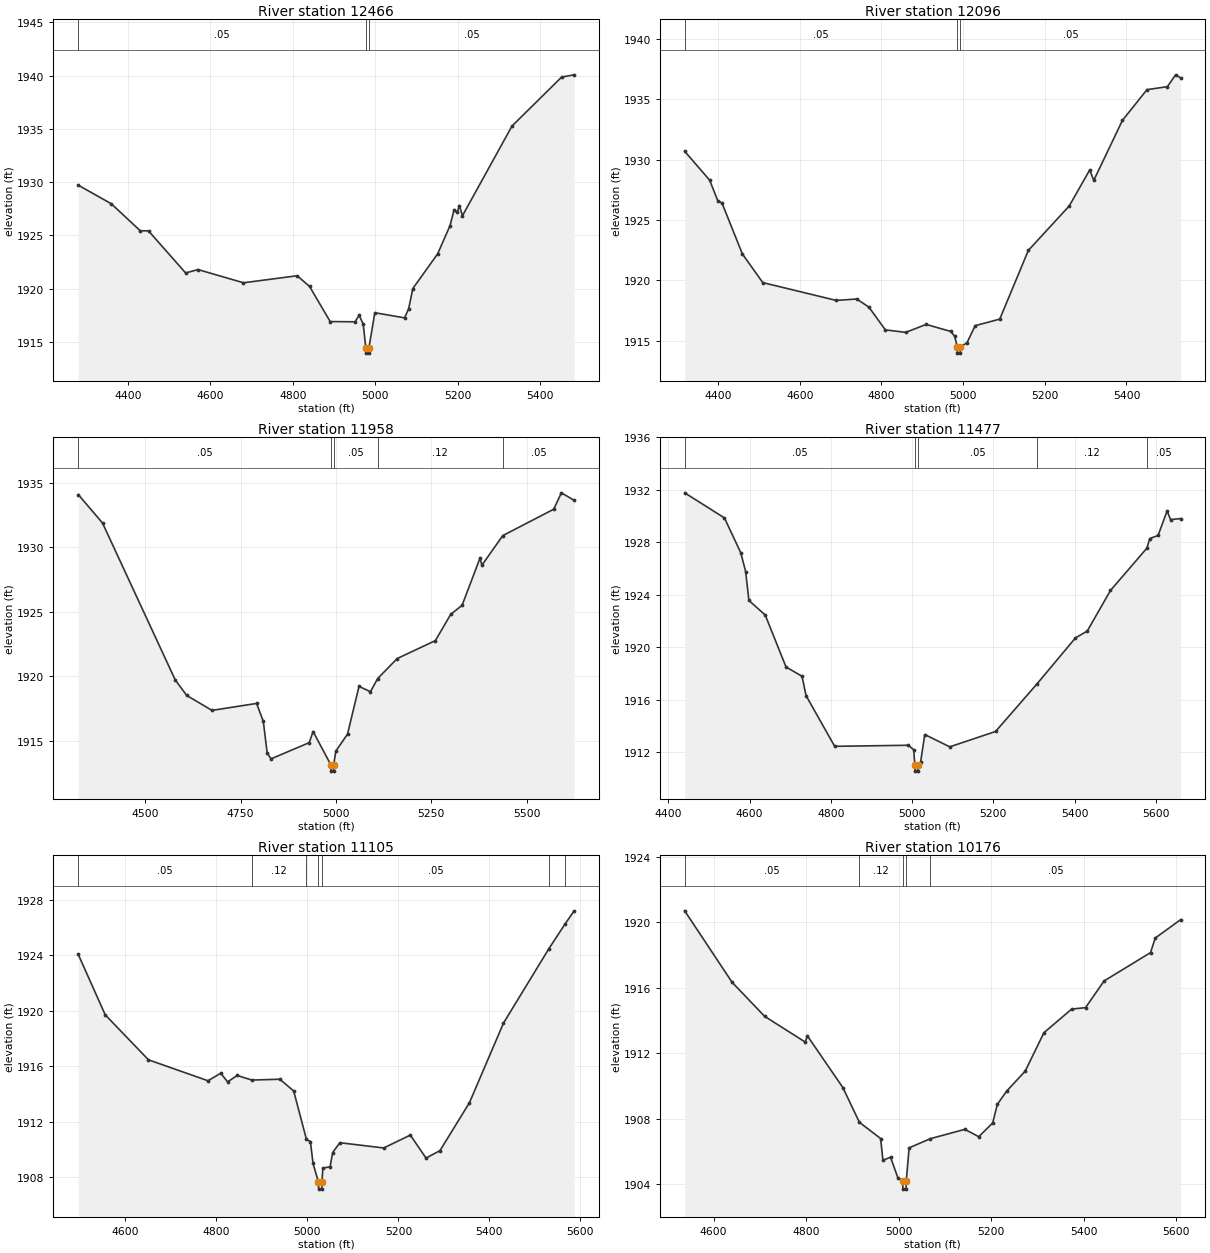
Type RM Length L Ch R = 1,12466,370,370,370
BEGIN DESCRIPTION:
Elm 01 94 12466.35
END DESCRIPTION:
XS GIS Cut Line= 3
      1600534.77      6793633.87      1601256.08      6793600.02
      1601735.26      6793631.27
#Sta/Elev= 30
  4279.9 1929.72  4360.2 1927.97  4430.3 1925.44  4450.3 1925.43  4540.4 1921.48
  4570.4 1921.80  4680.6 1920.56  4810.7 1921.22  4840.7 1920.22  4890.8 1916.92
  4950.9 1916.90  4960.9 1917.51  4970.9 1916.68  4977.1 1914.46  4977.6 1913.96
  4984.2 1913.96  4984.7 1914.46  4999.0 1917.75  5071.1 1917.27  5081.1 1918.14
  5091.1 1920.02  5151.2 1923.27  5181.3 1925.92  5191.3 1927.43  5198.9 1927.17
  5203.9 1927.81  5211.4 1926.85  5331.6 1935.27  5451.9 1939.86  5482.2 1940.07
#Mann=3,-1,0
  4279.9    0.05       0  4977.1    0.03       0  4984.7    0.05       0
Bank Sta=4977.1,4984.7
Exp/Cntr=0.3,0.1

Type RM Length L Ch R = 1,12096,138,138,138
BEGIN DESCRIPTION:
Elm 01 94 12096.3
END DESCRIPTION:
XS GIS Cut Line= 3
      1600573.77      6793881.27      1601253.47      6793876.06
      1601787.32      6793850.02
#Sta/Elev= 30
  4318.4 1930.70  4379.6 1928.30  4399.6 1926.58  4409.6 1926.42  4459.6 1922.19
  4509.6 1919.81  4689.6 1918.33  4739.6 1918.45  4769.6 1917.77  4809.6 1915.89
  4859.6 1915.68  4909.6 1916.34  4969.6 1915.76  4979.6 1915.36  4985.8 1914.46
  4986.3 1913.96  4993.0 1913.96  4993.5 1914.46  5009.7 1914.83  5029.7 1916.24
  5089.8 1916.78  5159.8 1922.48  5260.0 1926.17  5310.0 1929.15  5320.0 1928.29
  5390.1 1933.26  5450.2 1935.81  5500.2 1936.06  5520.3 1937.04  5532.6 1936.79
#Mann=3,-1,0
  4318.4    0.05       0  4985.8    0.05       0  4993.5    0.05       0
Bank Sta=4985.8,4993.5
Exp/Cntr=0.3,0.1

Type RM Length L Ch R = 1,11958,481,481,481
BEGIN DESCRIPTION:
Elm 01 94 11957.76
END DESCRIPTION:
XS GIS Cut Line= 3
      1600581.56      6794073.98      1601258.68      6794014.08
      1601878.43      6794045.33
#Sta/Elev= 30
  4324.4 1934.08  4388.1 1931.87  4578.8 1919.70  4608.9 1918.50  4675.1 1917.34
  4792.1 1917.88  4809.7 1916.49  4819.8 1914.04  4829.8 1913.58  4930.2 1914.84
  4940.2 1915.70  4986.6 1913.13  4987.1 1912.63  4993.8 1912.63  4994.3 1913.13
  4999.8 1914.18  5030.5 1915.50  5060.6 1919.20  5090.6 1918.79  5109.6 1919.81
  5160.7 1921.36  5260.8 1922.75  5300.9 1924.78  5330.9 1925.49  5377.9 1929.15
  5382.9 1928.60  5437.5 1930.89  5571.2 1932.94  5591.2 1934.21  5624.7 1933.63
#Mann=5,-1,0
  4324.4    0.05       0  4986.6    0.03       0  4994.3    0.05       0
  5109.6    0.12       0  5437.5    0.05       0
Bank Sta=4986.6,4994.3
Exp/Cntr=0.3,0.1

Type RM Length L Ch R = 1,11477,372,372,372
BEGIN DESCRIPTION:
Elm 01 94 11476.95
END DESCRIPTION:
XS GIS Cut Line= 3
      1600697.72      6794437.95      1601258.46      6794380.66
      1601899.11      6794234.82
#Sta/Elev= 30
  4440.3 1931.77  4538.1 1929.86  4578.3 1927.21  4590.4 1925.77  4598.4 1923.57
  4638.6 1922.46  4689.8 1918.50  4729.1 1917.80  4739.1 1916.32  4809.5 1912.46
  4990.4 1912.54  5004.0 1912.20  5006.8 1911.07  5007.3 1910.57  5014.0 1910.57
  5014.5 1911.07  5020.9 1911.23  5031.2 1913.36  5092.7 1912.42  5205.5 1913.59
  5306.8 1917.19  5402.2 1920.72  5431.2 1921.24  5488.3 1924.33  5578.1 1927.56
  5585.0 1928.29  5605.5 1928.52  5627.7 1930.39  5636.3 1929.73  5661.0 1929.81
#Mann=5,-1,0
  4440.3    0.05       0  5006.8    0.05       0  5014.5    0.05       0
  5306.8    0.12       0  5578.1    0.05       0
Bank Sta=5006.8,5014.5
Exp/Cntr=0.3,0.1

Type RM Length L Ch R = 1,11105,929,929,929
BEGIN DESCRIPTION:
Elm 01 94 11105.33
END DESCRIPTION:
XS GIS Cut Line= 3
      1600925.13      6794901.49      1601348.74      6794628.93
      1601857.43      6794337.25
#Sta/Elev= 30
  4496.2 1924.08  4555.5 1919.72  4650.6 1916.47  4781.4 1914.96  4809.4 1915.50
  4824.6 1914.88  4845.7 1915.34  4877.9 1915.01  4939.5 1915.07  4969.8 1914.22
  4997.8 1910.74  5006.6 1910.57  5012.4 1908.99  5024.3 1907.64  5024.8 1907.14
  5031.5 1907.14  5032.0 1907.64  5033.9 1908.66  5049.8 1908.75  5055.5 1909.78
  5071.3 1910.49  5167.7 1910.11  5226.2 1911.04  5260.7 1909.38  5291.4 1909.92
  5356.2 1913.38  5431.0 1919.12  5530.8 1924.49  5566.1 1926.26  5586.3 1927.22
#Mann=7,-1,0
  4496.2    0.05       0  4877.9    0.12       0  4997.8    0.05       0
  5024.3    0.03       0  5032.0    0.05       0  5530.8    0.12       0
  5566.1    0.05       0
Bank Sta=5024.3,5032
Exp/Cntr=0.3,0.1

Type RM Length L Ch R = 1,10176,319,319,319
BEGIN DESCRIPTION:
Elm 01 94 10175.88
END DESCRIPTION:
XS GIS Cut Line= 3
      1601003.43      6794944.81      1601461.72      6794888.82
      1602069.81      6794838.04
#Sta/Elev= 30
  4537.4 1920.70  4639.8 1916.34  4710.2 1914.26  4797.8 1912.69  4802.8 1913.06
  4879.3 1909.91  4915.0 1907.79  4960.9 1906.80  4965.9 1905.47  4982.3 1905.66
  4998.2 1904.40  5008.5 1904.21  5009.0 1903.71  5015.8 1903.71  5016.3 1904.21
  5022.5 1906.23  5068.4 1906.79  5142.9 1907.36  5173.0 1906.91  5203.1 1907.75
  5213.1 1908.88  5233.2 1909.69  5273.3 1910.91  5313.9 1913.26  5373.7 1914.70
  5403.8 1914.79  5443.9 1916.42  5544.3 1918.15  5554.5 1919.04  5609.3 1920.16
#Mann=5,-1,0
  4537.4    0.05       0  4915.0    0.12       0  5008.5    0.07       0
  5016.3    0.12       0  5068.4    0.05       0
Bank Sta=5008.5,5016.3
Exp/Cntr=0.3,0.1

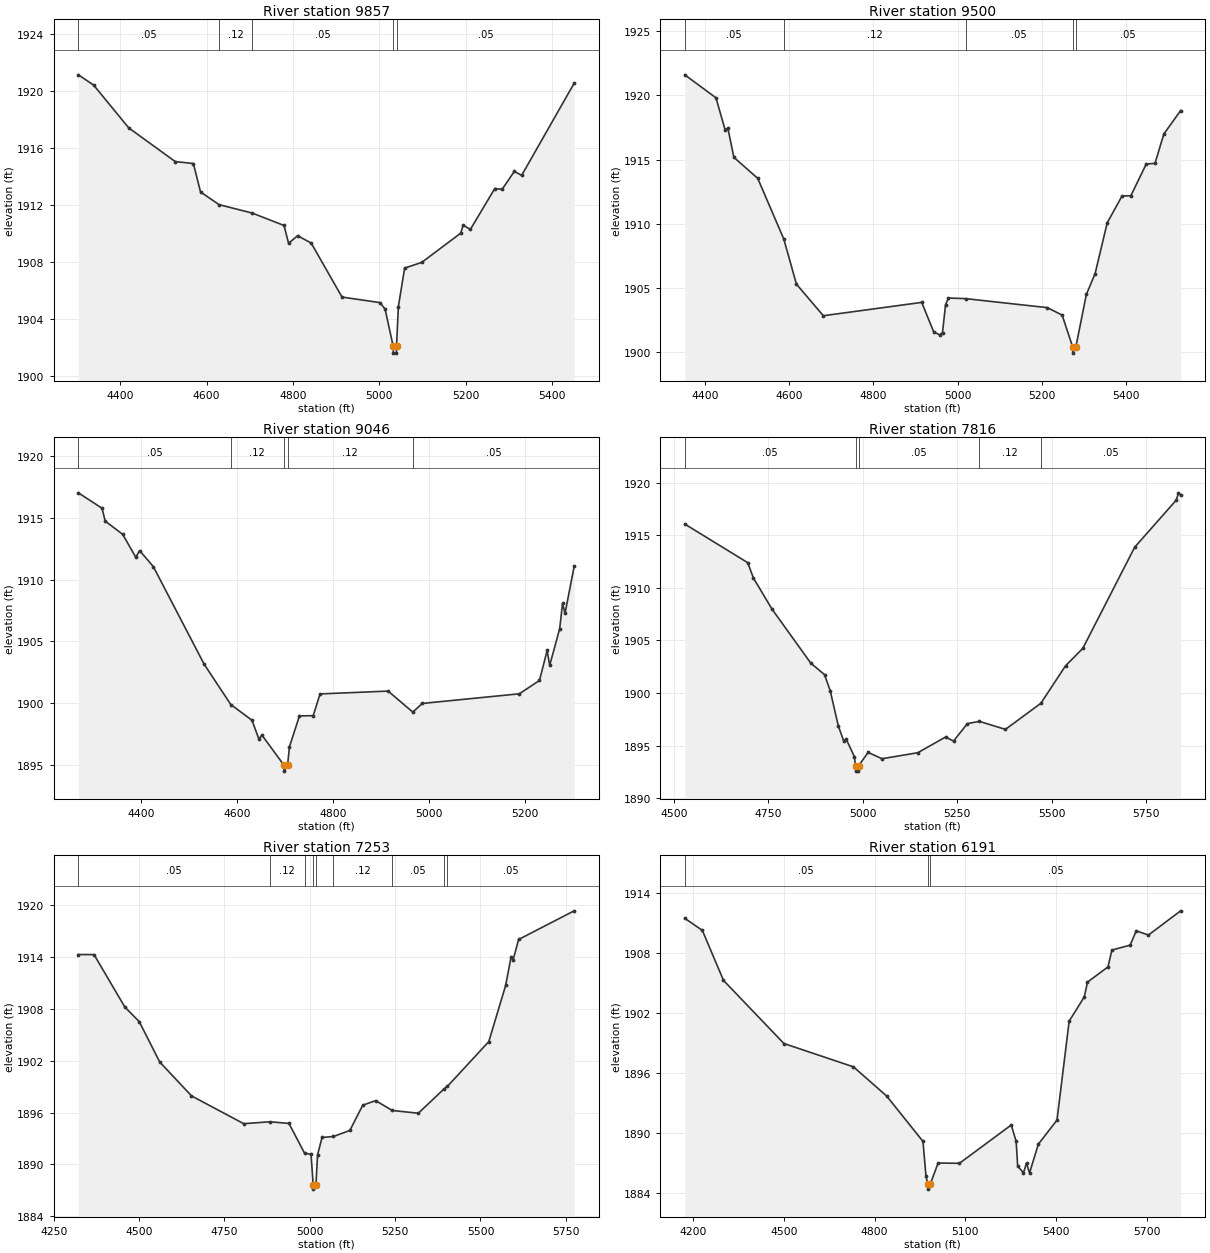
Type RM Length L Ch R = 1,9857,357,357,357
BEGIN DESCRIPTION:
Elm 01 94 9857.49
END DESCRIPTION:
XS GIS Cut Line= 3
      1601021.17      6795279.13      1601683.94      6795068.19
      1602091.38      6794870.95
#Sta/Elev= 30
  4303.1 1921.12  4338.6 1920.40  4419.8 1917.40  4527.5 1915.04  4569.5 1914.90
  4586.1 1912.91  4628.9 1912.02  4705.6 1911.43  4779.4 1910.56  4790.0 1909.31
  4810.8 1909.84  4842.3 1909.33  4913.7 1905.54  5002.0 1905.15  5013.5 1904.69
  5032.1 1902.11  5032.6 1901.61  5039.5 1901.61  5040.0 1902.11  5044.2 1904.87
  5058.7 1907.57  5098.3 1907.97  5188.6 1910.02  5194.2 1910.58  5210.9 1910.28
  5267.5 1913.15  5284.5 1913.09  5312.7 1914.35  5329.7 1914.07  5451.3 1920.53
#Mann=5,-1,0
  4303.1    0.05       0  4628.9    0.12       0  4705.6    0.05       0
  5032.1    0.05       0  5040.0    0.05       0
Bank Sta=5032.1,5040
Exp/Cntr=0.3,0.1

Type RM Length L Ch R = 1,9500,454,454,454
BEGIN DESCRIPTION:
Elm 01 94 9499.89
END DESCRIPTION:
XS GIS Cut Line= 3
      1601363.48      6795811.27      1601834.44      6795368.53
      1602168.61      6794956.24
#Sta/Elev= 30
  4352.1 1921.60  4426.1 1919.81  4447.6 1917.34  4454.4 1917.44  4468.6 1915.18
  4525.3 1913.54  4587.1 1908.82  4617.1 1905.31  4681.0 1902.85  4914.5 1903.89
  4942.8 1901.61  4957.0 1901.36  4963.9 1901.54  4971.2 1903.72  4978.0 1904.23
  5019.2 1904.18  5212.7 1903.48  5247.9 1902.90  5272.7 1900.44  5273.2 1899.94
  5280.6 1900.44  5305.4 1904.51  5326.2 1906.13  5354.9 1910.08  5390.1 1912.17
  5411.1 1912.19  5447.6 1914.66  5468.4 1914.71  5489.3 1916.99  5529.2 1918.82
#Mann=5,-1,0
  4352.1    0.05       0  4587.1    0.12       0  5019.2    0.05       0
  5272.7    0.07       0  5280.6    0.05       0
Bank Sta=5272.7,5280.6
Exp/Cntr=0.3,0.1

Type RM Length L Ch R = 1,9046,1230,1230,1230
BEGIN DESCRIPTION:
Elm 01 94 9045.76
END DESCRIPTION:
XS GIS Cut Line= 3
      1601667.33      6796099.88      1602133.92      6795537.80
      1602227.22      6795249.22
#Sta/Elev= 30
  4268.8 1917.03  4318.3 1915.78  4324.8 1914.74  4361.3 1913.67  4388.6 1911.81
  4396.5 1912.36  4425.1 1911.06  4531.2 1903.15  4586.7 1899.89  4630.9 1898.62
  4645.2 1897.10  4651.7 1897.41  4697.2 1895.00  4697.7 1894.50  4705.1 1895.00
  4709.0 1896.47  4729.8 1898.97  4758.5 1898.99  4772.8 1900.75  4914.7 1900.98
  4966.1 1899.28  4986.1 1899.98  5188.3 1900.76  5230.3 1901.84  5246.3 1904.27
  5251.6 1903.06  5272.4 1906.03  5278.4 1908.08  5283.6 1907.28  5302.6 1911.07
#Mann=5,-1,0
  4268.8    0.05       0  4586.7    0.12       0  4697.2    0.03       0
  4705.1    0.12       0  4966.1    0.05       0
Bank Sta=4697.2,4705.1
Exp/Cntr=0.3,0.1

Type RM Length L Ch R = 1,7816,563,563,563
BEGIN DESCRIPTION:
Elm 01 94 7816.42
END DESCRIPTION:
XS GIS Cut Line= 3
      1601720.03      6796302.58      1602118.47      6796049.98
      1602834.58      6795609.89
#Sta/Elev= 30
  4529.1 1916.06  4695.6 1912.39  4710.9 1910.92  4760.0 1907.97  4862.5 1902.84
  4899.0 1901.74  4913.9 1900.22  4935.4 1896.87  4949.4 1895.46  4956.6 1895.59
  4977.8 1893.96  4980.9 1893.07  4981.4 1892.57  4988.5 1892.57  4989.0 1893.07
  5014.3 1894.35  5051.0 1893.75  5145.7 1894.32  5219.1 1895.81  5240.4 1895.43
  5277.1 1897.09  5308.8 1897.30  5377.7 1896.54  5471.5 1899.02  5536.7 1902.58
  5582.5 1904.24  5719.8 1913.86  5829.9 1918.34  5835.7 1919.03  5841.4 1918.85
#Mann=5,-1,0
  4529.1    0.05       0  4980.9    0.03       0  4989.0    0.05       0
  5308.8    0.12       0  5471.5    0.05       0
Bank Sta=4980.9,4989
Exp/Cntr=0.3,0.1

Type RM Length L Ch R = 1,7253,1062,1062,1062
BEGIN DESCRIPTION:
Elm 01 94 7252.99
END DESCRIPTION:
XS GIS Cut Line= 3
      1601839.87      6796370.28      1602506.49      6796237.48
      1603183.61      6795865.06
#Sta/Elev= 30
  4322.0 1914.31  4368.0 1914.30  4458.2 1908.23  4500.6 1906.53  4560.3 1901.87
  4653.5 1897.94  4806.5 1894.72  4883.1 1894.94  4939.0 1894.75  4984.6 1891.31
  5003.7 1891.17  5010.0 1887.64  5010.5 1887.14  5018.1 1887.64  5022.8 1891.10
  5035.9 1893.12  5069.4 1893.24  5117.3 1893.93  5155.2 1896.86  5193.0 1897.39
  5241.5 1896.25  5318.1 1895.93  5392.2 1898.71  5403.4 1899.05  5524.5 1904.23
  5573.8 1910.73  5589.9 1914.07  5595.6 1913.67  5611.7 1916.05  5774.5 1919.37
#Mann=9,-1,0
  4322.0    0.05       0  4883.1    0.12       0  4984.6    0.05       0
  5010.0    0.05       0  5018.1    0.05       0  5069.4    0.12       0
  5241.5    0.05       0  5392.2    0.12       0  5403.4    0.05       0
Bank Sta=5010,5018.1
Exp/Cntr=0.3,0.1

Type RM Length L Ch R = 1,6191,374,374,374
BEGIN DESCRIPTION:
Elm 01 94 6190.95
END DESCRIPTION:
XS GIS Cut Line= 3
      1601877.06      6796590.78      1602706.03      6796608.14
      1603510.59      6796501.88
#Sta/Elev= 30
  4171.7 1911.49  4229.7 1910.29  4299.7 1905.29  4499.7 1898.98  4729.8 1896.65
  4839.8 1893.73  4959.8 1889.20  4969.8 1885.72  4975.7 1884.93  4976.2 1884.43
  4983.9 1884.93  5009.9 1887.04  5080.5 1887.01  5252.0 1890.84  5268.2 1889.19
  5273.2 1886.74  5292.3 1886.05  5302.4 1887.02  5312.5 1886.05  5341.6 1888.92
  5403.3 1891.33  5443.6 1901.22  5493.7 1903.64  5504.2 1905.12  5572.2 1906.64
  5584.9 1908.32  5645.4 1908.81  5665.5 1910.24  5705.9 1909.82  5812.4 1912.24
#Mann=3,-1,0
  4171.7    0.05       0  4975.7    0.05       0  4983.9    0.05       0
Bank Sta=4975.7,4983.9
Exp/Cntr=0.3,0.1

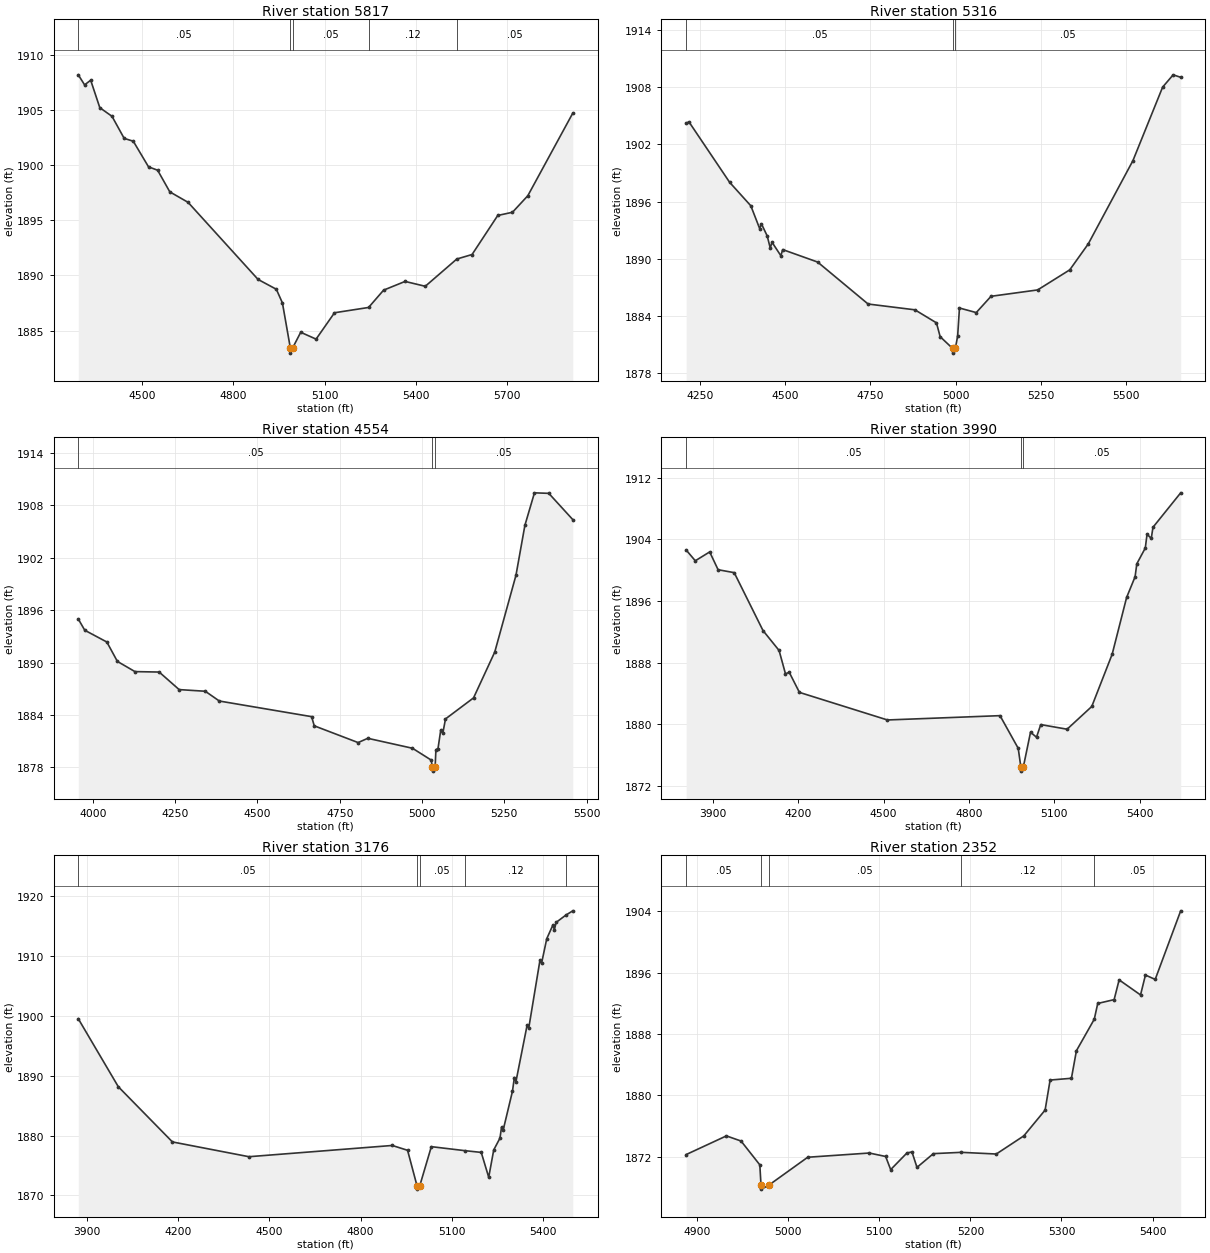
Type RM Length L Ch R = 1,5817,501,501,501
BEGIN DESCRIPTION:
Elm 01 94 5816.62
END DESCRIPTION:
XS GIS Cut Line= 3
      1602054.22      6796933.66      1602766.07      6796938.00
      1603671.59      6796821.02
#Sta/Elev= 30
  4290.0 1908.19  4310.8 1907.28  4330.8 1907.70  4360.8 1905.21  4400.8 1904.43
  4440.8 1902.43  4470.8 1902.17  4520.8 1899.85  4550.8 1899.54  4590.8 1897.58
  4650.8 1896.63  4880.8 1889.64  4940.8 1888.75  4960.8 1887.51  4986.6 1883.46
  4987.1 1882.96  4994.9 1883.46  5020.9 1884.85  5071.4 1884.23  5131.9 1886.62
  5243.9 1887.10  5293.2 1888.67  5363.8 1889.46  5430.2 1889.02  5533.7 1891.49
  5583.9 1891.90  5668.3 1895.44  5716.7 1895.73  5767.1 1897.23  5914.9 1904.72
#Mann=5,-1,0
  4290.0    0.05       0  4986.6    0.05       0  4994.9    0.05       0
  5243.9    0.12       0  5533.7    0.05       0
Bank Sta=4986.6,4994.9
Exp/Cntr=0.3,0.1

Type RM Length L Ch R = 1,5316,762,762,762
BEGIN DESCRIPTION:
Elm 01 94 5316.36
END DESCRIPTION:
XS GIS Cut Line= 3
      1602410.18      6797434.96      1603156.70      6797176.71
      1603780.88      6796955.65
#Sta/Elev= 30
  4208.8 1904.23  4217.0 1904.38  4336.4 1898.03  4398.7 1895.56  4424.6 1893.17
  4429.9 1893.66  4446.7 1892.40  4455.7 1891.13  4461.0 1891.73  4486.9 1890.31
  4492.2 1890.96  4594.8 1889.65  4743.0 1885.24  4880.5 1884.63  4943.8 1883.26
  4954.6 1881.81  4991.0 1880.58  4991.5 1880.08  4999.3 1880.58  5006.0 1881.88
  5011.3 1884.82  5060.6 1884.34  5104.0 1886.05  5240.9 1886.72  5335.2 1888.83
  5389.4 1891.55  5520.6 1900.30  5607.9 1908.03  5638.8 1909.32  5660.9 1909.06
#Mann=3,-1,0
  4208.8    0.05       0  4991.0    0.05       0  4999.3    0.05       0
Bank Sta=4991,4999.3
Exp/Cntr=0.3,0.1

Type RM Length L Ch R = 1,4554,564,564,564
BEGIN DESCRIPTION:
Elm 01 94 4553.92
END DESCRIPTION:
XS GIS Cut Line= 4
      1602623.71      6797880.71      1603342.03      6797611.61
      1603504.79      6797390.26      1603870.74      6797110.92
#Sta/Elev= 30
  3955.9 1895.00  3975.6 1893.71  4042.7 1892.36  4074.7 1890.14  4128.1 1888.97
  4201.7 1888.92  4262.3 1886.91  4341.7 1886.72  4384.4 1885.60  4664.7 1883.81
  4672.7 1882.76  4806.0 1880.84  4835.3 1881.33  4971.1 1880.19  5027.8 1878.84
  5031.5 1878.07  5032.0 1877.57  5039.9 1878.07  5042.3 1880.02  5048.6 1880.15
  5056.9 1882.25  5063.2 1881.90  5071.4 1883.55  5156.6 1885.96  5221.0 1891.21
  5285.5 1900.01  5312.6 1905.73  5341.6 1909.45  5385.2 1909.39  5458.1 1906.38
#Mann=3,-1,0
  3955.9    0.05       0  5031.5    0.05       0  5039.9    0.05       0
Bank Sta=5031.5,5039.9
Exp/Cntr=0.3,0.1

Type RM Length L Ch R = 1,3990,814,814,814
BEGIN DESCRIPTION:
Elm 01 94 3990.09
END DESCRIPTION:
XS GIS Cut Line= 3
      1602964.79      6798723.88      1603648.82      6797748.18
      1603957.84      6797296.81
#Sta/Elev= 30
  3805.6 1902.63  3837.7 1901.23  3888.3 1902.38  3917.9 1900.07  3974.6 1899.69
  4075.7 1892.18  4132.3 1889.59  4154.7 1886.57  4168.1 1886.75  4203.8 1884.15
  4513.2 1880.57  4909.0 1881.13  4973.0 1876.89  4982.4 1874.43  4982.9 1873.93
  4990.8 1874.43  5016.3 1878.98  5037.3 1878.33  5052.2 1879.97  5144.9 1879.37
  5231.6 1882.32  5303.3 1889.10  5354.1 1896.47  5383.9 1899.16  5390.0 1900.84
  5419.8 1902.89  5425.9 1904.67  5440.8 1904.14  5446.8 1905.58  5544.2 1910.05
#Mann=3,-1,0
  3805.6    0.05       0  4982.4    0.05       0  4990.8    0.05       0
Bank Sta=4982.4,4990.8
Exp/Cntr=0.3,0.1

Type RM Length L Ch R = 1,3176,824,824,824
BEGIN DESCRIPTION:
Elm 01 94 2930.479
END DESCRIPTION:
XS GIS Cut Line= 3
      1603343.71      6798910.71      1603999.05      6797990.28
      1604114.09      6797504.52
#Sta/Elev= 30
  3870.1 1899.54  4002.0 1888.17  4180.3 1878.94  4432.3 1876.47  4904.6 1878.35
  4954.9 1877.54  4986.3 1871.55  4986.8 1871.05  4994.7 1871.55  5033.2 1878.15
  5143.9 1877.48  5197.6 1877.19  5222.2 1873.03  5238.7 1877.60  5259.3 1879.58
  5264.4 1881.40  5269.6 1880.88  5300.4 1887.41  5306.7 1889.71  5311.8 1889.00
  5348.9 1898.51  5354.1 1897.98  5391.2 1909.37  5396.3 1908.81  5413.4 1912.92
  5433.4 1915.18  5438.6 1914.43  5444.2 1915.64  5476.5 1916.87  5499.2 1917.58
#Mann=5,-1,0
  3870.1    0.05       0  4986.3    0.05       0  4994.7    0.05       0
  5143.9    0.12       0  5476.5    0.05       0
Bank Sta=4986.3,4994.7
Exp/Cntr=0.3,0.1

Type RM Length L Ch R = 1,2352,369,369,369
BEGIN DESCRIPTION:
Elm 01 94 2352.29
END DESCRIPTION:
XS GIS Cut Line= 3
      1604460.10      6797896.68      1604434.06      6797787.35
      1604262.52      6797392.27
#Sta/Elev= 30
  4887.8 1872.31  4932.0 1874.74  4948.1 1874.07  4968.7 1870.97  4970.0 1868.31
  4970.5 1867.81  4978.4 1868.31  5021.3 1871.96  5088.9 1872.51  5106.9 1872.06
  5112.4 1870.35  5130.3 1872.52  5135.8 1872.65  5141.3 1870.64  5159.3 1872.43
  5189.9 1872.60  5228.4 1872.38  5258.6 1874.74  5282.0 1878.10  5287.5 1882.01
  5310.9 1882.24  5316.4 1885.83  5336.0 1889.93  5339.8 1891.98  5357.8 1892.48
  5363.3 1895.05  5386.8 1893.09  5392.2 1895.68  5402.9 1895.11  5430.9 1904.04
#Mann=5,-1,0
  4887.8    0.05       0  4970.0    0.05       0  4978.4    0.05       0
  5189.9    0.12       0  5336.0    0.05       0
Bank Sta=4970,4978.4
Exp/Cntr=0.3,0.1

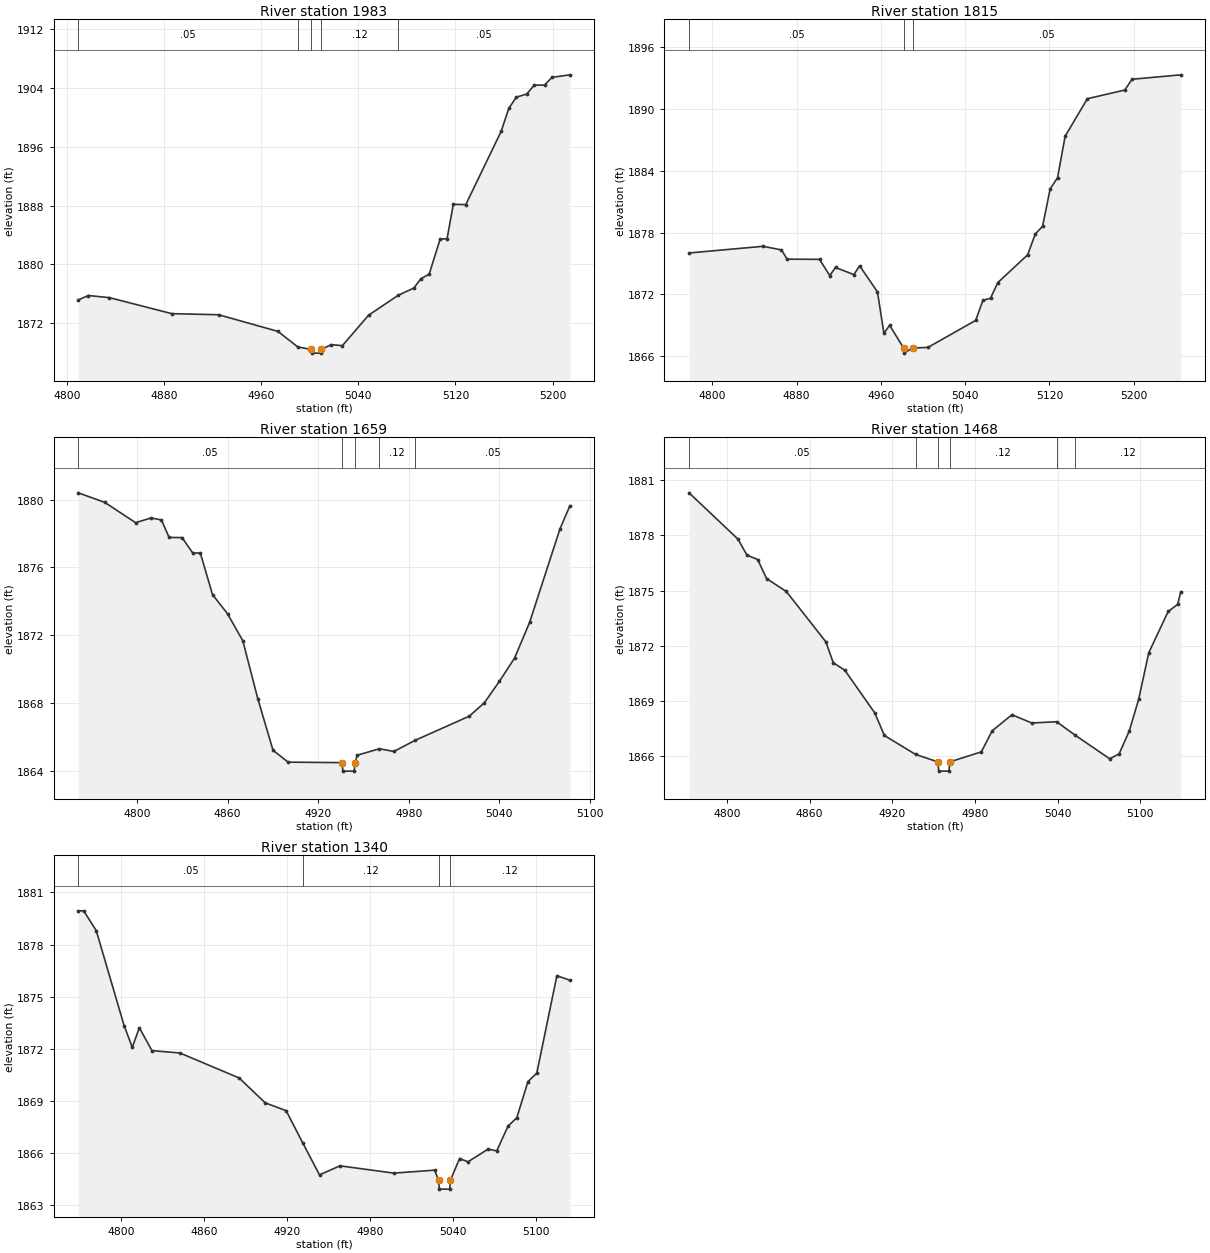
Type RM Length L Ch R = 1,1983,168,168,168
BEGIN DESCRIPTION:
Mapping XS 95871616
END DESCRIPTION:
XS GIS Cut Line= 4
      1604579.85      6797575.46      1604489.57      6797533.79
      1604305.54      6797427.88      1604250.52      6797352.24
#Sta/Elev= 30
  4809.0 1875.14  4817.4 1875.75  4834.8 1875.46  4886.2 1873.28  4924.8 1873.13
  4973.7 1870.86  4990.0 1868.75  5001.0 1868.40  5001.5 1867.90  5008.9 1867.90
  5009.4 1868.40  5017.5 1869.05  5026.8 1868.92  5048.4 1873.07  5072.9 1875.79
  5085.7 1876.77  5091.5 1878.04  5098.3 1878.65  5107.3 1883.41  5113.1 1883.50
  5118.2 1888.17  5128.5 1888.14  5157.7 1898.14  5164.0 1901.27  5170.2 1902.78
  5178.7 1903.20  5184.9 1904.42  5193.4 1904.42  5199.6 1905.48  5214.3 1905.82
#Mann=5,-1,0
  4809.0    0.05       0  4990.0    0.12       0  5001.0    0.07       0
  5009.4    0.12       0  5072.9    0.05       0
Bank Sta=5001,5009.4
Exp/Cntr=0.3,0.1

Type RM Length L Ch R = 1,1815,156,156,156
BEGIN DESCRIPTION:
Elm 01 94 1814.82
END DESCRIPTION:
XS GIS Cut Line= 3
      1604587.71      6797550.36      1604493.96      6797347.24
      1604326.06      6797171.59
#Sta/Elev= 30
  4778.0 1876.03  4848.2 1876.68  4865.6 1876.33  4871.1 1875.43  4901.8 1875.41
  4911.5 1873.84  4917.0 1874.62  4934.4 1873.93  4939.9 1874.78  4956.8 1872.25
  4962.9 1868.24  4968.4 1869.00  4981.6 1866.80  4982.1 1866.30  4990.1 1866.80
  5004.6 1866.85  5050.0 1869.48  5056.9 1871.43  5064.1 1871.63  5071.0 1873.15
  5099.3 1875.85  5106.6 1877.88  5113.5 1878.62  5120.7 1882.26  5127.7 1883.34
  5134.9 1887.37  5156.0 1891.02  5191.5 1891.86  5198.4 1892.91  5244.7 1893.34
#Mann=3,-1,0
  4778.0    0.05       0  4981.6    0.05       0  4990.1    0.05       0
Bank Sta=4981.6,4990.1
Exp/Cntr=0.3,0.1

Type RM Length L Ch R = 1,1659,191,191,191
BEGIN DESCRIPTION:
Mapping XS fd56c7b6
END DESCRIPTION:
XS GIS Cut Line= 3
      1604617.35      6797525.17      1604634.70      6797449.26
      1604623.92      6797201.36
#Sta/Elev= 30
  4760.9 1880.40  4778.5 1879.84  4799.0 1878.64  4809.3 1878.92  4816.1 1878.80
  4821.2 1877.77  4829.8 1877.76  4836.9 1876.85  4841.9 1876.85  4850.0 1874.40
  4860.0 1873.26  4870.1 1871.67  4880.1 1868.23  4890.1 1865.22  4900.1 1864.52
  4935.9 1864.49  4936.4 1863.99  4943.9 1863.99  4944.4 1864.49  4946.0 1864.93
  4960.6 1865.31  4970.2 1865.15  4984.4 1865.81  5020.2 1867.23  5030.2 1868.02
  5040.2 1869.29  5050.2 1870.65  5060.2 1872.76  5080.3 1878.27  5086.9 1879.64
#Mann=5,-1,0
  4760.9    0.05       0  4935.9    0.05       0  4944.4    0.05       0
  4960.6    0.12       0  4984.4    0.05       0
Bank Sta=4935.9,4944.4
Exp/Cntr=0.3,0.1

Type RM Length L Ch R = 1,1468,128,128,128
BEGIN DESCRIPTION:
Mapping XS c0afefba
END DESCRIPTION:
XS GIS Cut Line= 4
      1604625.39      6797527.95      1604694.38      6797444.64
      1604842.82      6797323.54      1604882.03      6797281.81
#Sta/Elev= 30
  4772.5 1880.32  4808.0 1877.80  4814.5 1876.93  4822.3 1876.69  4828.8 1875.65
  4843.1 1874.95  4871.8 1872.21  4877.2 1871.07  4885.6 1870.66  4907.3 1868.34
  4914.3 1867.11  4936.9 1866.08  4953.2 1865.67  4953.7 1865.17  4961.2 1865.17
  4961.7 1865.67  4984.7 1866.22  4992.6 1867.37  5006.9 1868.24  5021.3 1867.79
  5039.3 1867.86  5052.5 1867.14  5077.9 1865.84  5084.7 1866.11  5092.0 1867.34
  5098.9 1869.08  5106.2 1871.61  5120.3 1873.86  5127.2 1874.25  5129.5 1874.94
#Mann=6,-1,0
  4772.5    0.05       0  4936.9    0.12       0  4953.2    0.07       0
  4961.7    0.12       0  5039.3    0.05       0  5052.5    0.12       0
Bank Sta=4953.2,4961.7
Exp/Cntr=0.3,0.1

Type RM Length L Ch R = 1,1340,62,62,62
BEGIN DESCRIPTION:
Mapping XS 7cf1cf8b
END DESCRIPTION:
XS GIS Cut Line= 4
      1604631.91      6797526.67      1604745.17      6797516.25
      1604902.72      6797452.45      1604958.71      6797408.17
#Sta/Elev= 30
  4769.1 1879.94  4773.1 1879.94  4782.2 1878.80  4802.3 1873.34  4808.2 1872.09
  4813.3 1873.22  4822.4 1871.90  4842.5 1871.77  4885.4 1870.33  4904.2 1868.90
  4919.3 1868.45  4931.2 1866.61  4943.4 1864.76  4958.2 1865.28  4997.0 1864.86
  5026.5 1865.03  5029.4 1864.44  5029.9 1863.94  5037.4 1863.94  5037.9 1864.44
  5044.5 1865.70  5050.6 1865.51  5065.1 1866.24  5071.4 1866.14  5079.5 1867.56
  5085.9 1868.05  5093.9 1870.12  5100.3 1870.61  5114.8 1876.21  5124.2 1875.95
#Mann=4,-1,0
  4769.1    0.05       0  4931.2    0.12       0  5029.4    0.07       0
  5037.9    0.12       0
Bank Sta=5029.4,5037.9
Exp/Cntr=0.3,0.1