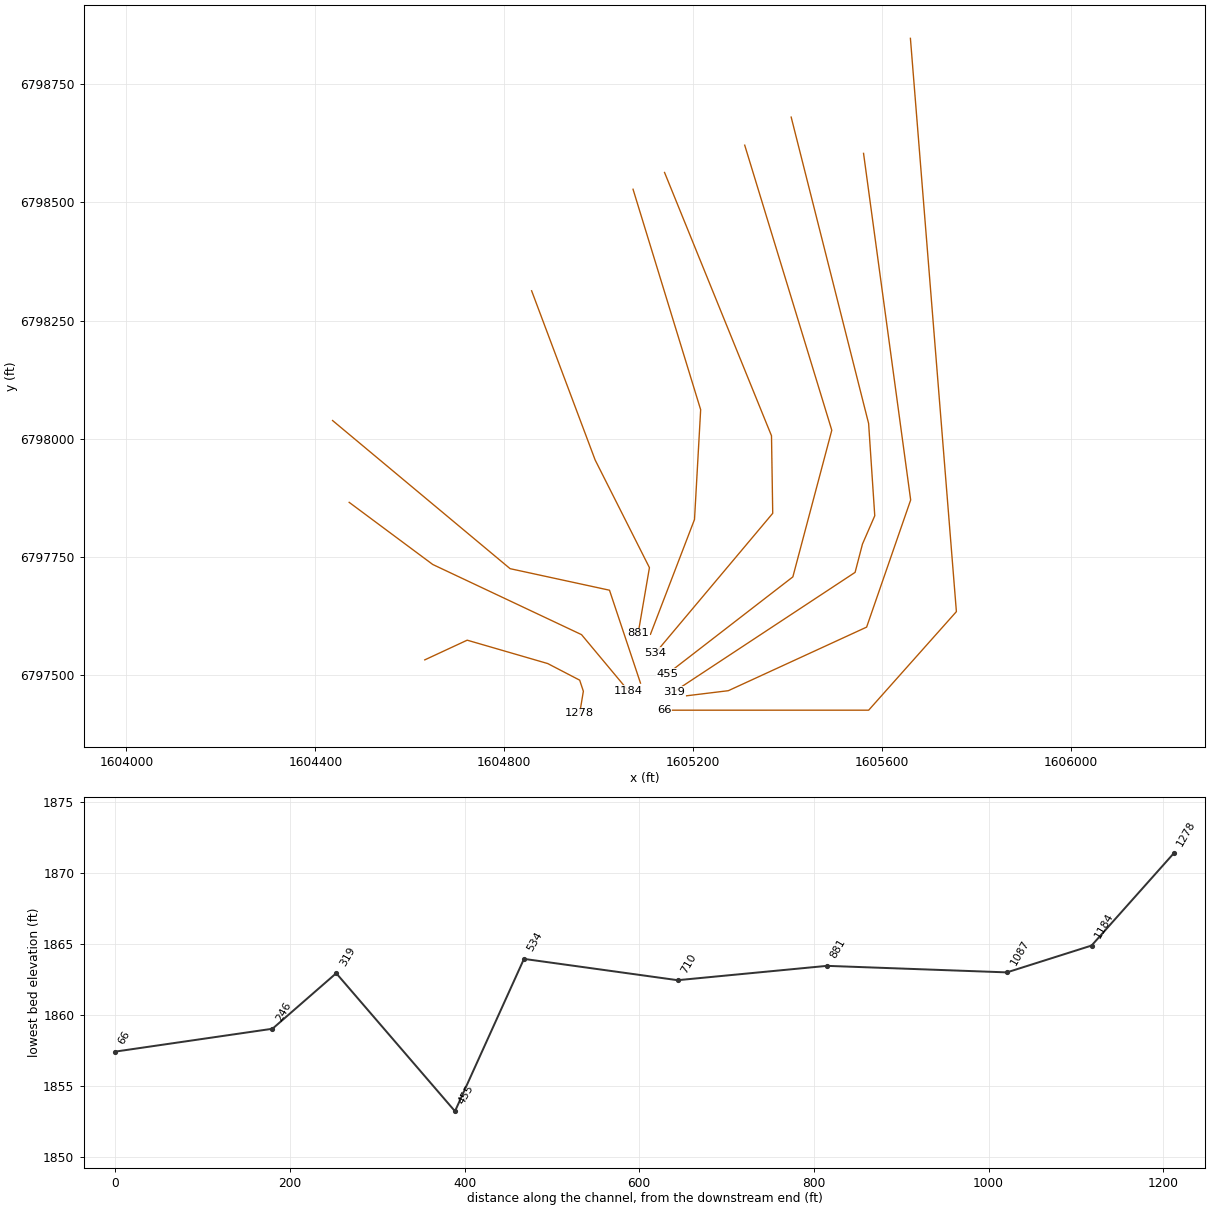
HEC-RAS study Elm 01 94.prj: Elm 01 94 Base Level Engineering

--- Elm 01 94.g01 (geometry) --- (continued)

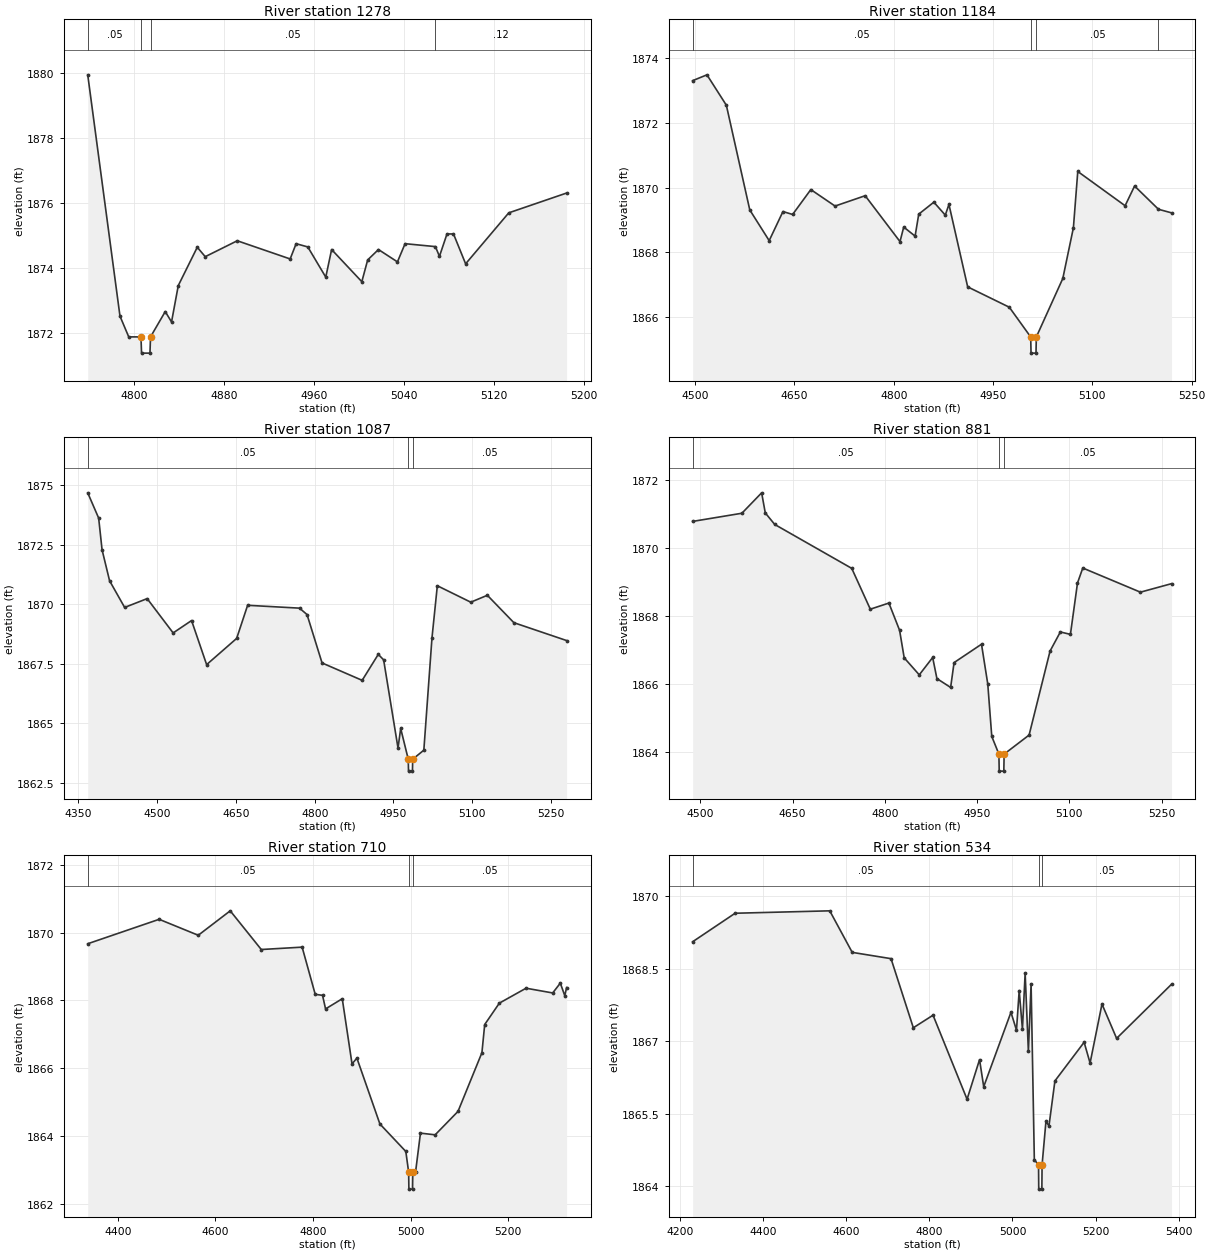
Type RM Length L Ch R = 1,1278,94,94,94
BEGIN DESCRIPTION:
Mapping XS 095bdb05
END DESCRIPTION:
XS GIS Cut Line= 6
      1604631.86      6797531.86      1604721.73      6797573.54
      1604892.30      6797524.06      1604960.01      6797488.91
      1604967.82      6797465.47      1604960.01      6797418.62
#Sta/Elev= 30
  4758.5 1879.94  4787.2 1872.51  4795.0 1871.87  4805.9 1871.87  4806.4 1871.37
  4813.9 1871.37  4814.4 1871.87  4827.5 1872.65  4833.1 1872.33  4839.1 1873.45
  4856.0 1874.63  4863.1 1874.34  4891.6 1874.83  4938.7 1874.27  4944.0 1874.74
  4954.4 1874.64  4970.4 1873.71  4975.6 1874.56  5002.5 1873.57  5007.7 1874.24
  5017.3 1874.56  5034.2 1874.18  5041.0 1874.74  5068.0 1874.65  5071.6 1874.35
  5078.3 1875.04  5084.1 1875.04  5094.9 1874.12  5133.3 1875.69  5184.8 1876.30
#Mann=4,-1,0
  4758.5    0.05       0  4805.9    0.05       0  4814.4    0.05       0
  5068.0    0.12       0
Bank Sta=4805.9,4814.4
Exp/Cntr=0.3,0.1

Type RM Length L Ch R = 1,1184,97,97,97
BEGIN DESCRIPTION:
Mapping XS 75a140c9
END DESCRIPTION:
XS GIS Cut Line= 4
      1604471.70      6797865.23      1604648.81      6797733.70
      1604963.92      6797585.26      1605062.87      6797466.77
#Sta/Elev= 30
  4496.2 1873.31  4517.8 1873.49  4547.1 1872.55  4582.5 1869.31  4611.8 1868.36
  4632.6 1869.26  4647.2 1869.17  4674.7 1869.94  4711.3 1869.43  4756.8 1869.75
  4809.4 1868.33  4815.0 1868.78  4832.2 1868.50  4837.7 1869.18  4860.5 1869.55
  4877.8 1869.15  4883.3 1869.48  4911.6 1866.93  4974.5 1866.30  5006.8 1865.38
  5007.3 1864.88  5014.8 1864.88  5015.3 1865.38  5055.3 1867.19  5071.3 1868.76
  5077.9 1870.50  5149.4 1869.44  5163.7 1870.05  5199.8 1869.33  5219.5 1869.22
#Mann=4,-1,0
  4496.2    0.05       0  5006.8    0.05       0  5015.3    0.05       0
  5199.8    0.12       0
Bank Sta=5006.8,5015.3
Exp/Cntr=0.3,0.1

Type RM Length L Ch R = 1,1087,206,206,206
BEGIN DESCRIPTION:
Mapping XS 60a917ba
END DESCRIPTION:
XS GIS Cut Line= 4
      1604436.54      6798038.41      1604812.65      6797724.86
      1605023.15      6797679.29      1605088.81      6797482.71
#Sta/Elev= 30
  4367.6 1874.67  4388.4 1873.61  4394.9 1872.28  4409.2 1870.98  4437.9 1869.86
  4480.8 1870.23  4530.3 1868.79  4565.4 1869.31  4594.1 1867.46  4651.3 1868.56
  4672.2 1869.95  4771.1 1869.83  4785.4 1869.56  4814.0 1867.53  4890.4 1866.80
  4921.1 1867.89  4931.3 1867.66  4958.7 1863.96  4963.8 1864.78  4978.2 1863.49
  4978.7 1862.99  4986.2 1862.99  4986.7 1863.49  5007.9 1863.87  5023.4 1868.58
  5033.6 1870.77  5097.3 1870.08  5128.9 1870.37  5179.4 1869.22  5279.9 1868.47
#Mann=3,-1,0
  4367.6    0.05       0  4978.2    0.05       0  4986.7    0.05       0
Bank Sta=4978.2,4986.7
Exp/Cntr=0.3,0.1

Type RM Length L Ch R = 1,881,171,171,171
BEGIN DESCRIPTION:
Mapping XS 22f917e1
END DESCRIPTION:
XS GIS Cut Line= 4
      1604858.21      6798312.99      1604992.77      6797954.90
      1605107.79      6797727.03      1605083.92      6797588.16
#Sta/Elev= 30
  4487.4 1870.79  4567.5 1871.03  4599.6 1871.63  4605.5 1871.04  4620.9 1870.70
  4746.1 1869.41  4776.3 1868.21  4806.5 1868.39  4823.9 1867.59  4831.4 1866.78
  4855.9 1866.28  4877.7 1866.79  4884.6 1866.17  4906.9 1865.91  4912.5 1866.64
  4957.1 1867.18  4967.3 1866.01  4973.8 1864.47  4985.4 1863.95  4985.9 1863.45
  4993.4 1863.45  4993.9 1863.95  5034.5 1864.51  5068.6 1866.98  5085.3 1867.54
  5101.7 1867.47  5113.2 1868.98  5121.8 1869.42  5215.5 1868.71  5266.1 1868.96
#Mann=3,-1,0
  4487.4    0.05       0  4985.4    0.05       0  4993.9    0.05       0
Bank Sta=4985.4,4993.9
Exp/Cntr=0.3,0.1

Type RM Length L Ch R = 1,710,176,176,176
BEGIN DESCRIPTION:
Mapping XS 008c430e
END DESCRIPTION:
XS GIS Cut Line= 4
      1605073.06      6798527.84      1605216.30      6798061.23
      1605203.27      6797829.03      1605109.97      6797585.99
#Sta/Elev= 30
  4338.6 1869.67  4484.9 1870.39  4565.0 1869.92  4630.5 1870.64  4694.1 1869.50
  4777.8 1869.57  4804.6 1868.18  4819.6 1868.15  4825.8 1867.75  4860.0 1868.05
  4880.0 1866.13  4890.0 1866.30  4937.1 1864.36  4990.2 1863.55  4996.0 1862.94
  4996.5 1862.44  5004.0 1862.44  5004.5 1862.94  5010.2 1862.95  5020.2 1864.09
  5050.3 1864.04  5097.1 1864.73  5146.1 1866.46  5151.8 1867.29  5181.8 1867.92
  5236.5 1868.36  5291.1 1868.22  5306.7 1868.51  5315.8 1868.14  5319.6 1868.38
#Mann=3,-1,0
  4338.6    0.05       0  4996.0    0.05       0  5004.5    0.05       0
Bank Sta=4996,5004.5
Exp/Cntr=0.3,0.1

Type RM Length L Ch R = 1,534,79,79,79
BEGIN DESCRIPTION:
Elm 01 94 535.7
END DESCRIPTION:
XS GIS Cut Line= 4
      1605139.80      6798563.37      1605366.36      6798006.10
      1605368.96      6797842.03      1605120.83      6797546.94
#Sta/Elev= 30
  4231.2 1869.06  4333.3 1869.65  4560.8 1869.70  4614.8 1868.84  4708.1 1868.71
  4761.7 1867.28  4809.1 1867.54  4890.9 1865.80  4920.9 1866.62  4930.9 1866.06
  4996.4 1867.60  5009.7 1867.23  5016.2 1868.05  5024.0 1867.25  5030.5 1868.41
  5038.3 1866.79  5044.8 1868.19  5052.6 1864.55  5062.7 1864.44  5063.2 1863.94
  5070.7 1863.94  5071.2 1864.44  5080.5 1865.34  5087.8 1865.25  5102.1 1866.18
  5172.3 1866.98  5186.6 1866.55  5215.2 1867.77  5250.4 1867.06  5382.4 1868.18
#Mann=3,-1,0
  4231.2    0.05       0  5062.7    0.05       0  5071.2    0.05       0
Bank Sta=5062.7,5071.2
Exp/Cntr=0.3,0.1

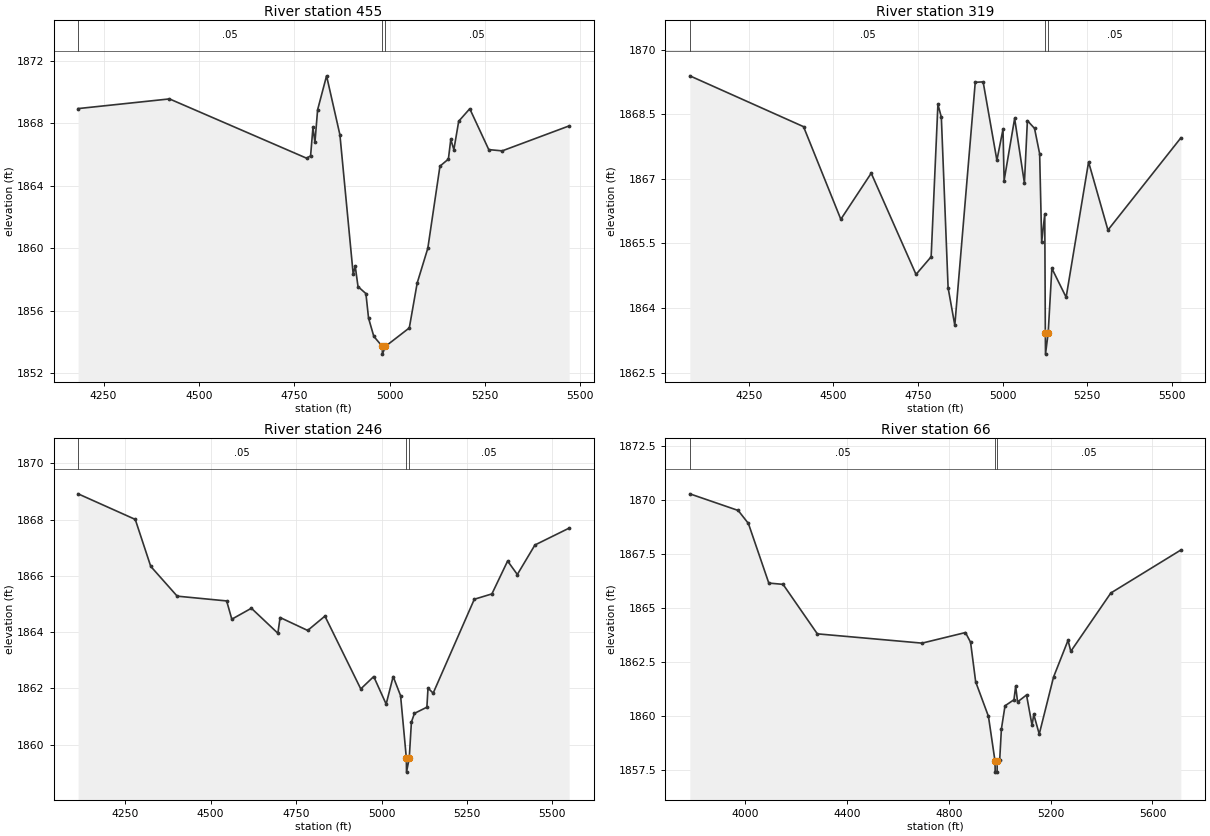
Type RM Length L Ch R = 1,455,136,136,136
BEGIN DESCRIPTION:
Mapping XS 91b385a3
END DESCRIPTION:
XS GIS Cut Line= 4
      1605309.61      6798621.15      1605494.07      6798017.83
      1605411.61      6797707.50      1605145.76      6797502.17
#Sta/Elev= 30
  4183.1 1868.95  4422.8 1869.57  4782.4 1865.77  4792.9 1865.92  4799.1 1867.74
  4804.3 1866.78  4811.3 1868.87  4834.8 1871.05  4869.8 1867.27  4904.7 1858.32
  4909.9 1858.86  4917.3 1857.54  4938.0 1857.09  4944.9 1855.52  4958.7 1854.35
  4980.8 1853.71  4981.3 1853.21  4989.3 1853.71  5051.8 1854.89  5072.5 1857.77
  5100.4 1860.00  5132.2 1865.26  5154.3 1865.71  5160.6 1866.97  5168.7 1866.32
  5181.4 1868.14  5210.4 1868.94  5260.2 1866.32  5295.5 1866.24  5471.0 1867.84
#Mann=3,-1,0
  4183.1    0.05       0  4980.8    0.05       0  4989.3    0.05       0
Bank Sta=4980.8,4989.3
Exp/Cntr=0.3,0.1

Type RM Length L Ch R = 1,319,73,73,73
BEGIN DESCRIPTION:
Elm 01 94 319.06
END DESCRIPTION:
XS GIS Cut Line= 6
      1605408.03      6798680.56      1605572.08      6798032.14
      1605585.11      6797836.83      1605559.06      6797776.93
      1605543.44      6797717.03      1605159.94      6797464.49
#Sta/Elev= 30
  4075.8 1869.39  4411.8 1868.21  4522.0 1866.06  4611.8 1867.13  4744.2 1864.78
  4788.9 1865.19  4808.9 1868.73  4819.0 1868.43  4839.0 1864.47  4858.8 1863.60
  4919.2 1869.24  4942.5 1869.25  4983.2 1867.43  5001.2 1868.15  5004.5 1866.96
  5035.6 1868.40  5064.5 1866.90  5073.3 1868.35  5094.4 1868.17  5109.5 1867.58
  5115.5 1865.53  5124.6 1866.18  5126.3 1863.43  5126.8 1862.93  5134.8 1863.43
  5145.6 1864.92  5187.8 1864.25  5254.1 1867.39  5311.3 1865.81  5526.8 1867.95
#Mann=3,-1,0
  4075.8    0.05       0  5126.3    0.05       0  5134.8    0.05       0
Bank Sta=5126.3,5134.8
Exp/Cntr=0.3,0.1

Type RM Length L Ch R = 1,246,180,180,180
BEGIN DESCRIPTION:
Mapping XS 914989d8
END DESCRIPTION:
XS GIS Cut Line= 5
      1605561.35      6798603.76      1605661.17      6797870.26
      1605567.86      6797601.17      1605274.89      6797466.62
      1605185.92      6797455.77
#Sta/Elev= 30
  4112.0 1868.92  4279.3 1868.01  4324.6 1866.34  4402.0 1865.28  4546.8 1865.11
  4561.9 1864.46  4619.2 1864.85  4696.7 1863.96  4703.2 1864.52  4783.9 1864.06
  4834.4 1864.57  4939.3 1861.98  4977.2 1862.42  5013.6 1861.44  5034.1 1862.42
  5055.8 1861.74  5072.7 1859.52  5073.2 1859.02  5081.2 1859.52  5087.5 1860.80
  5096.4 1861.11  5132.8 1861.33  5136.1 1862.01  5151.2 1861.83  5271.6 1865.17
  5323.1 1865.36  5369.1 1866.53  5397.5 1866.05  5449.0 1867.10  5549.1 1867.70
#Mann=3,-1,0
  4112.0    0.05       0  5072.7    0.05       0  5081.2    0.05       0
Bank Sta=5072.7,5081.2
Exp/Cntr=0.3,0.1

Type RM Length L Ch R = 1,66,0,0,0
BEGIN DESCRIPTION:
Elm 01 94 1976.129
END DESCRIPTION:
XS GIS Cut Line= 4
      1605660.63      6798847.24      1605758.03      6797633.95
      1605572.20      6797425.38      1605139.94      6797425.37
#Sta/Elev= 30
  3782.8 1870.29  3972.7 1869.52  4012.8 1868.92  4093.0 1866.16  4149.0 1866.10
  4283.6 1863.81  4695.0 1863.38  4865.5 1863.87  4885.6 1863.42  4905.6 1861.59
  4955.8 1859.99  4981.7 1857.91  4982.2 1857.41  4989.7 1857.41  4990.2 1857.91
  5000.0 1857.98  5006.7 1859.41  5020.9 1860.48  5056.0 1860.76  5062.7 1861.39
  5070.2 1860.66  5105.3 1860.98  5127.1 1859.58  5133.8 1860.08  5155.3 1859.17
  5211.5 1861.81  5268.4 1863.51  5279.3 1863.00  5436.5 1865.70  5711.6 1867.69
#Mann=3,-1,0
  3782.8    0.05       0  4981.7    0.03       0  4990.2    0.05       0
Bank Sta=4981.7,4990.2
Exp/Cntr=0.3,0.1

Chan Stop Cuts=-1