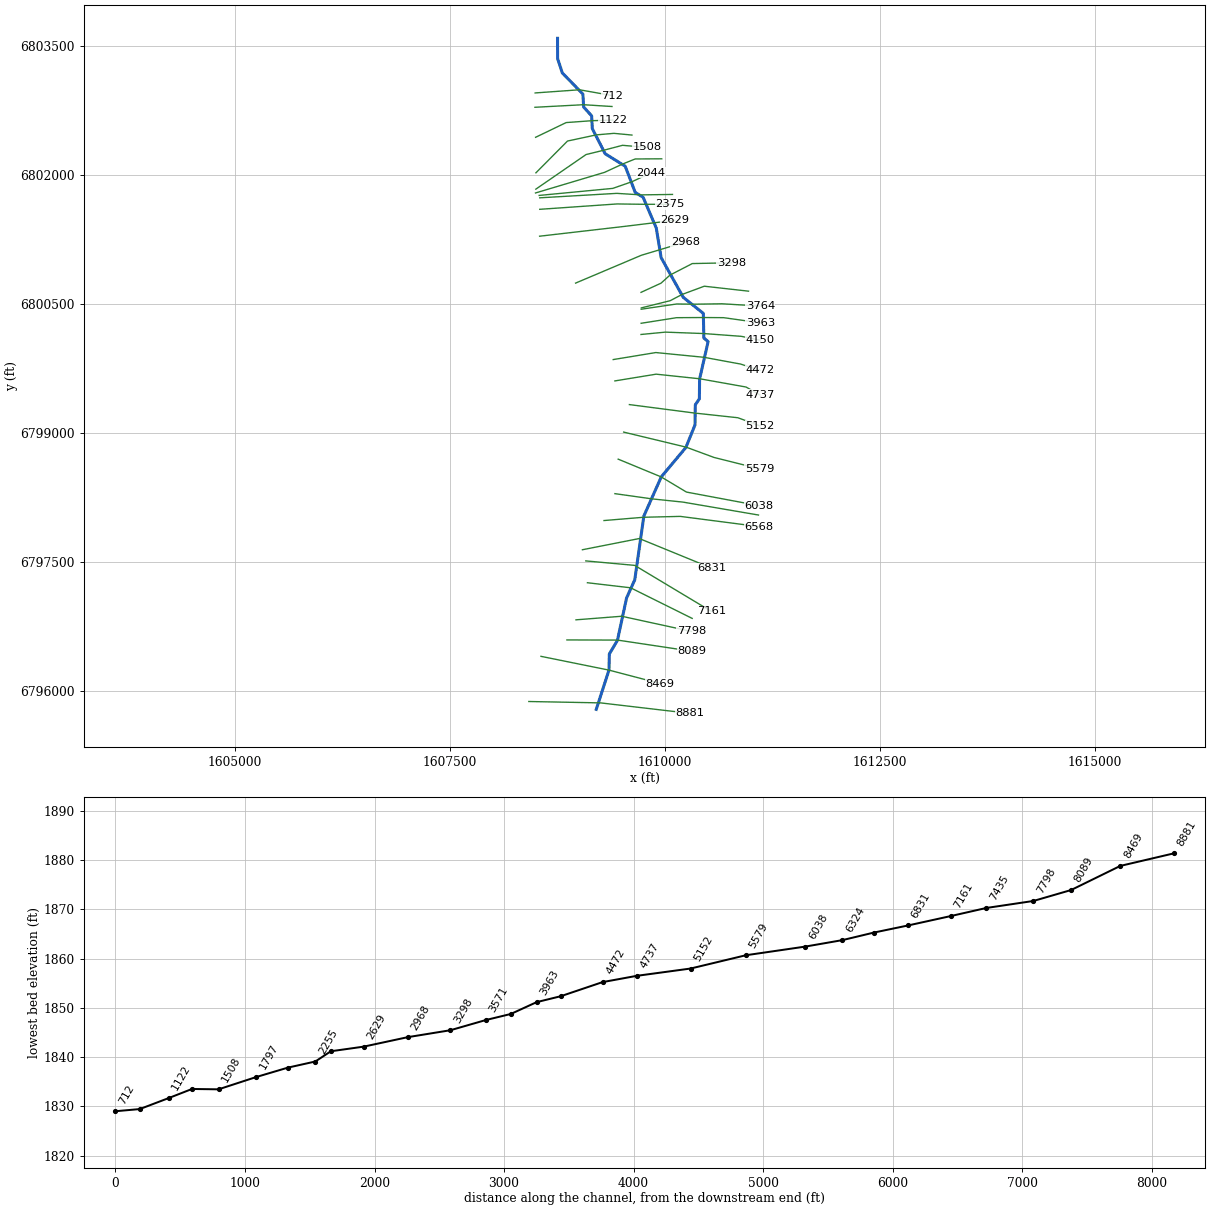
--- Elm 01 95.prj (project) ---

Proj Title=Elm 01 95 Base Level Engineering
Current Plan=p01
Default Exp/Contr=0.3,0.1
English Units
Geom File=g01
Flow File=f01
Plan File=p01
BEGIN DESCRIPTION:
Elm 01 95
END DESCRIPTION:

--- Elm 01 95.p01 (plan) ---

Plan Title=Multiple Run
Short Identifier=Multiple
Geom File=g01
Flow File=f01
Subcritical Flow
K Sum by GR= 0
Std Step Tol= 0.01
Critical Tol= 0.01
Num of Std Step Trials= 20
Max Error Tol= 0.3
Flow Tol Ratio= 0.001
Split Flow NTrial= 30
Split Flow Tol= 0.02
Split Flow Ratio= 0.02
Log Output Level= 0
Friction Slope Method= 1
Unsteady Friction Slope Method= 2
Unsteady Bridges Friction Slope Method= 1
Parabolic Critical Depth
Global Vel Dist=  1 , 1 , 1
Global Log Level= 0
CheckData=True
Encroach Param= -1, 0, 0, 0
BEGIN DESCRIPTION:
Multiple Run
END DESCRIPTION:

--- Elm 01 95.f01 (steady flow) ---

Flow Title=Multiple
Number of Profiles=7
Profile Names=10-year,25-year,50-year,1pct_min,100-year,1pct_plu,500-year
River Rch & RM= Elm 01 95,Reach-1,8881
     234     325     401     307     492     676     750
River Rch & RM= Elm 01 95,Reach-1,5152
     338     478     596     460     738    1010    1150
Boundary for River Rch & Prof#=Elm 01 95,Reach-1,1
Up Type=0
Dn Type=3
Dn Slope=0.001
Boundary for River Rch & Prof#=Elm 01 95,Reach-1,2
Up Type=0
Dn Type=3
Dn Slope=0.001
Boundary for River Rch & Prof#=Elm 01 95,Reach-1,3
Up Type=0
Dn Type=3
Dn Slope=0.001
Boundary for River Rch & Prof#=Elm 01 95,Reach-1,4
Up Type=0
Dn Type=3
Dn Slope=0.001
Boundary for River Rch & Prof#=Elm 01 95,Reach-1,5
Up Type=0
Dn Type=3
Dn Slope=0.001
Boundary for River Rch & Prof#=Elm 01 95,Reach-1,6
Up Type=0
Dn Type=3
Dn Slope=0.001
Boundary for River Rch & Prof#=Elm 01 95,Reach-1,7
Up Type=0
Dn Type=3
Dn Slope=0.001

--- Elm 01 95.g01 (geometry) ---

Geom Title=Existing Conditions

River Reach=Elm 01 95,Reach-1
Reach XY= 30
      1609205.00      6795788.00      1609352.74      6796243.94
      1609357.24      6796432.07      1609451.17      6796589.58
      1609557.27      6797082.06      1609652.74      6797293.94
      1609758.75      6798036.45      1609960.83      6798490.30
      1610246.84      6798831.95      1610352.74      6799093.94
      1610356.22      6799327.50      1610403.78      6799398.50
      1610406.22      6799627.50      1610505.15      6800063.11
      1610455.96      6800103.96      1610449.54      6800390.45
      1610215.63      6800578.00      1609958.83      6801039.58
      1609902.74      6801382.06      1609749.54      6801740.66
      1609658.19      6801796.35      1609541.61      6802101.33
      1609308.50      6802246.46      1609158.76      6802539.56
      1609151.44      6802686.53      1609058.56      6802789.47
      1609049.30      6802940.38      1608810.52      6803185.57
      1608755.52      6803353.22      1608755.00      6803588.00

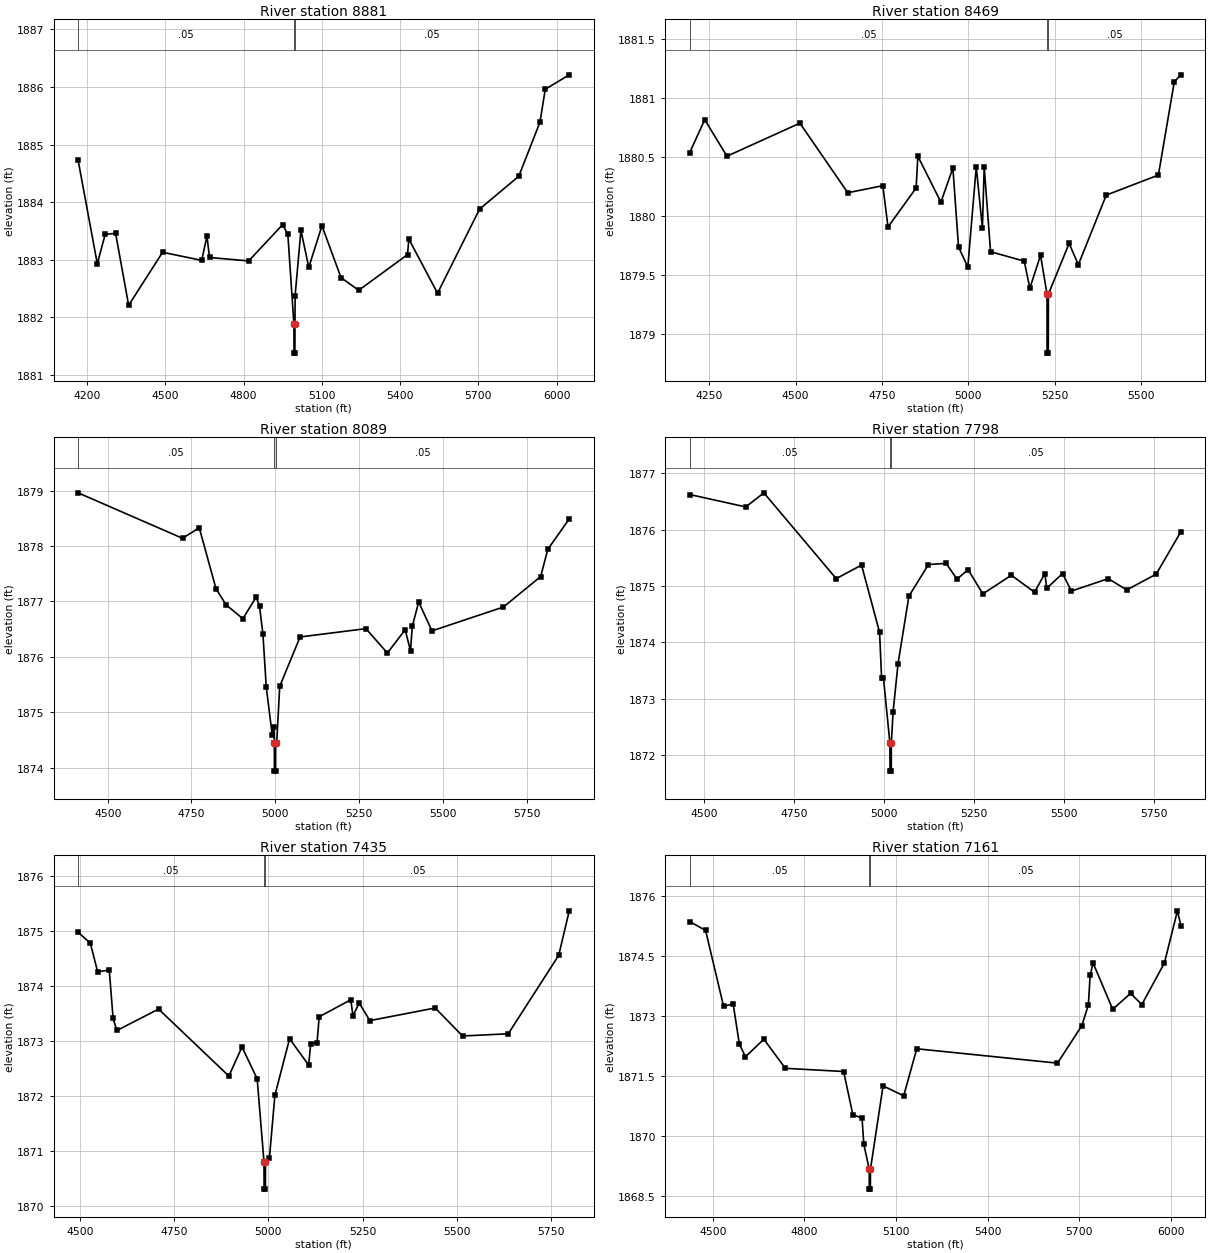
Type RM Length L Ch R = 1,8881,412,412,412
BEGIN DESCRIPTION:
Elm 01 95 8000.048
END DESCRIPTION:
XS GIS Cut Line= 3
      1608421.37      6795879.03      1609255.21      6795862.91
      1610296.40      6795741.00
#Sta/Elev= 30
  4166.0 1884.73  4239.6 1882.93  4269.7 1883.44  4309.7 1883.46  4359.7 1882.21
  4489.7 1883.13  4639.7 1882.99  4659.7 1883.41  4669.7 1883.04  4819.8 1882.98
  4949.8 1883.61  4969.8 1883.44  4993.1 1881.88  4993.4 1881.38  4996.9 1881.38
  4997.1 1881.88  4997.7 1882.38  5019.9 1883.51  5050.1 1882.87  5100.5 1883.59
  5173.6 1882.69  5241.4 1882.47  5428.4 1883.09  5433.5 1883.36  5543.5 1882.42
  5704.6 1883.88  5854.9 1884.45  5936.1 1885.39  5956.3 1885.96  6048.3 1886.21
#Mann=3,-1,0
  4166.0    0.05       0  4993.1    0.05       0  4997.1    0.05       0
Bank Sta=4993.1,4997.1
Exp/Cntr=0.3,0.1

Type RM Length L Ch R = 1,8469,380,380,380
BEGIN DESCRIPTION:
Elm 01 95 7568.924
END DESCRIPTION:
XS GIS Cut Line= 3
      1608562.38      6796403.98      1609352.74      6796243.94
      1609947.84      6796087.99
#Sta/Elev= 30
  4193.6 1880.54  4237.1 1880.82  4301.4 1880.51  4512.6 1880.79  4651.2 1880.20
  4752.6 1880.26  4767.6 1879.91  4848.9 1880.24  4854.0 1880.51  4920.7 1880.12
  4955.4 1880.41  4971.7 1879.74  4998.6 1879.57  5023.0 1880.42  5040.8 1879.90
  5046.0 1880.42  5064.4 1879.70  5162.0 1879.62  5178.1 1879.39  5209.1 1879.67
  5227.8 1879.34  5228.0 1878.84  5231.5 1878.84  5231.8 1879.34  5291.8 1879.77
  5318.5 1879.59  5399.3 1880.18  5550.2 1880.35  5596.1 1881.14  5615.2 1881.20
#Mann=3,-1,0
  4193.6    0.05       0  5227.8    0.05       0  5231.8    0.05       0
Bank Sta=5227.8,5231.8
Exp/Cntr=0.3,0.1

Type RM Length L Ch R = 1,8089,291,291,291
BEGIN DESCRIPTION:
Elm 01 95 8089.42
END DESCRIPTION:
XS GIS Cut Line= 3
      1608863.54      6796594.72      1609452.08      6796592.98
      1610319.33      6796462.89
#Sta/Elev= 30
  4411.7 1878.96  4723.2 1878.14  4773.2 1878.33  4823.2 1877.23  4853.2 1876.94
  4903.2 1876.69  4943.2 1877.08  4953.2 1876.91  4963.2 1876.41  4973.2 1875.45
  4991.0 1874.59  4996.0 1874.74  4997.2 1874.44  4997.5 1873.94  5001.0 1873.94
  5001.2 1874.44  5004.2 1874.44  5013.3 1875.47  5074.0 1876.36  5270.5 1876.51
  5334.5 1876.07  5387.5 1876.49  5403.6 1876.11  5408.7 1876.55  5427.9 1876.99
  5467.6 1876.47  5680.7 1876.90  5791.9 1877.45  5813.1 1877.94  5877.2 1878.49
#Mann=3,-1,0
  4411.7    0.05       0  4997.2    0.05       0  5001.2    0.05       0
Bank Sta=4997.2,5001.2
Exp/Cntr=0.3,0.1

Type RM Length L Ch R = 1,7798,363,363,363
BEGIN DESCRIPTION:
Elm 01 95 7797.78
END DESCRIPTION:
XS GIS Cut Line= 3
      1608969.79      6796828.40      1609501.04      6796870.06
      1610311.73      6796693.37
#Sta/Elev= 30
  4461.1 1876.62  4616.8 1876.40  4666.9 1876.65  4867.6 1875.13  4937.8 1875.37
  4987.9 1874.18  4993.5 1873.37  4998.6 1873.37  5016.5 1872.22  5016.8 1871.72
  5020.3 1871.72  5020.5 1872.22  5025.4 1872.77  5039.0 1873.62  5069.3 1874.82
  5123.5 1875.38  5172.6 1875.40  5202.7 1875.12  5233.4 1875.29  5274.4 1874.86
  5353.5 1875.19  5417.7 1874.89  5446.5 1875.22  5451.6 1874.96  5495.6 1875.22
  5520.0 1874.91  5622.4 1875.13  5673.5 1874.93  5755.4 1875.21  5823.7 1875.96
#Mann=3,-1,0
  4461.1    0.05       0  5016.5    0.05       0  5020.5    0.05       0
Bank Sta=5016.5,5020.5
Exp/Cntr=0.3,0.1

Type RM Length L Ch R = 1,7435,274,274,274
BEGIN DESCRIPTION:
Elm 01 95 7434.86
END DESCRIPTION:
XS GIS Cut Line= 3
      1609102.72      6797259.53      1609604.05      6797200.94
      1610320.06      6796845.10
#Sta/Elev= 30
  4494.6 1874.98  4527.1 1874.78  4546.5 1874.26  4577.4 1874.29  4587.5 1873.41
  4597.6 1873.19  4708.3 1873.58  4895.0 1872.36  4929.8 1872.89  4970.1 1872.31
  4988.2 1870.80  4988.5 1870.30  4992.0 1870.30  4992.2 1870.80  5002.7 1870.87
  5017.2 1872.01  5056.2 1873.04  5106.8 1872.56  5112.4 1872.95  5129.2 1872.97
  5134.8 1873.44  5218.8 1873.75  5224.4 1873.46  5241.2 1873.69  5269.2 1873.37
  5442.8 1873.60  5515.6 1873.09  5636.9 1873.13  5770.9 1874.56  5798.9 1875.37
#Mann=3,-1,0
  4494.6    0.05       0  4988.2    0.05       0  4992.2    0.05       0
Bank Sta=4988.2,4992.2
Exp/Cntr=0.3,0.1

Type RM Length L Ch R = 1,7161,330,330,330
BEGIN DESCRIPTION:
Elm 01 95 7160.79
END DESCRIPTION:
XS GIS Cut Line= 3
      1609083.21      6797513.44      1609651.79      6797461.35
      1610540.78      6796927.96
#Sta/Elev= 30
  4424.7 1875.37  4476.7 1875.15  4535.5 1873.25  4567.1 1873.30  4587.2 1872.30
  4607.3 1871.98  4667.5 1872.42  4737.8 1871.69  4928.6 1871.61  4958.7 1870.53
  4988.8 1870.44  4994.8 1869.78  5012.4 1869.16  5012.6 1868.66  5016.1 1868.66
  5016.4 1869.16  5057.7 1871.25  5125.2 1871.00  5167.9 1872.18  5628.6 1871.82
  5708.3 1872.76  5729.7 1873.28  5735.5 1874.03  5745.2 1874.33  5809.4 1873.17
  5867.7 1873.57  5904.6 1873.29  5978.5 1874.33  6021.2 1875.64  6032.4 1875.27
#Mann=3,-1,0
  4424.7    0.05       0  5012.4    0.05       0  5016.4    0.05       0
Bank Sta=5012.4,5016.4
Exp/Cntr=0.3,0.1

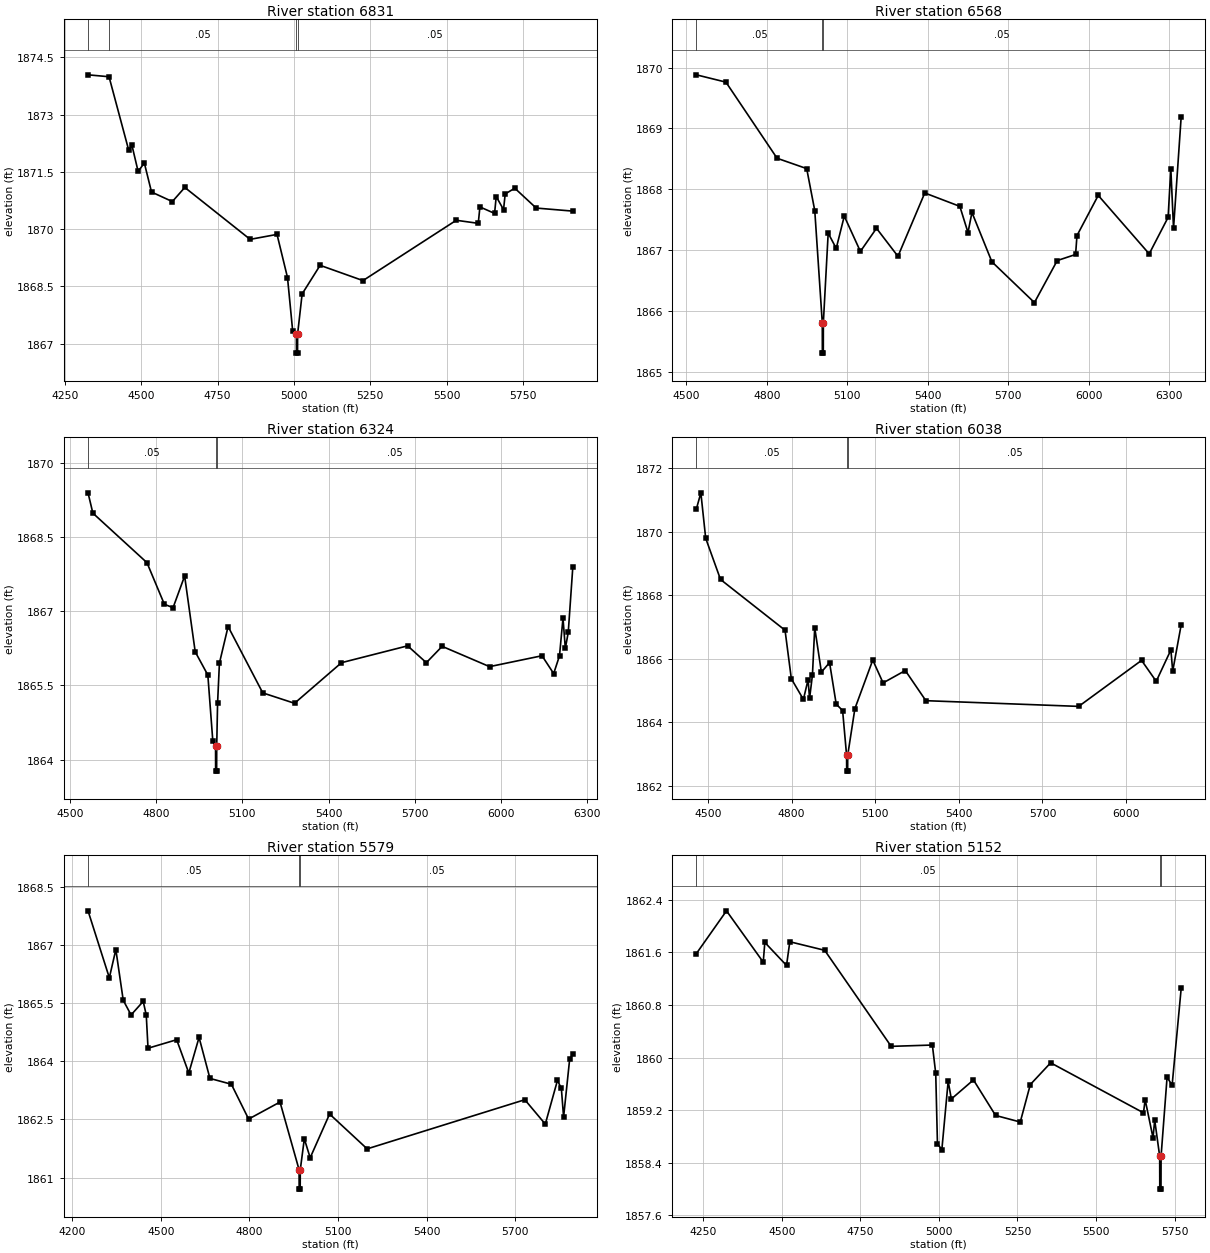
Type RM Length L Ch R = 1,6831,263,263,263
BEGIN DESCRIPTION:
Elm 01 95 6830.87
END DESCRIPTION:
XS GIS Cut Line= 3
      1609044.10      6797643.20      1609705.61      6797773.42
      1610550.96      6797427.48
#Sta/Elev= 30
  4325.7 1874.04  4394.5 1873.99  4459.1 1872.06  4469.3 1872.20  4489.7 1871.51
  4510.1 1871.73  4533.6 1870.97  4601.8 1870.72  4642.6 1871.09  4856.6 1869.73
  4944.6 1869.86  4978.9 1868.73  4996.0 1867.32  5008.0 1867.25  5008.3 1866.75
  5011.8 1866.75  5012.0 1867.25  5026.8 1868.30  5085.7 1869.05  5226.1 1868.65
  5531.6 1870.23  5603.6 1870.15  5609.0 1870.58  5657.0 1870.41  5662.4 1870.85
  5686.4 1870.51  5691.8 1870.92  5723.2 1871.07  5793.3 1870.55  5913.3 1870.47
#Mann=4,-1,0
  4325.7    0.12       0  4394.5    0.05       0  5008.0    0.05       0
  5012.0    0.05       0
Bank Sta=5008,5012
Exp/Cntr=0.3,0.1

Type RM Length L Ch R = 1,6568,244,244,244
BEGIN DESCRIPTION:
Elm 01 95 6567.73
END DESCRIPTION:
XS GIS Cut Line= 4
      1609295.15      6797982.62      1609757.00      6798020.82
      1610181.77      6798030.81      1611093.26      6797912.88
#Sta/Elev= 30
  4537.1 1869.88  4647.3 1869.76  4838.0 1868.51  4948.4 1868.34  4978.5 1867.65
  5006.5 1865.81  5006.8 1865.31  5010.3 1865.31  5010.5 1865.81  5028.5 1867.28
  5058.5 1867.03  5088.5 1867.56  5148.6 1866.98  5208.6 1867.36  5288.6 1866.90
  5388.6 1867.94  5519.4 1867.72  5549.7 1867.29  5564.5 1867.62  5638.8 1866.81
  5797.4 1866.14  5882.4 1866.83  5950.9 1866.93  5956.0 1867.24  6035.3 1867.90
  6225.3 1866.94  6295.8 1867.54  6305.9 1868.34  6316.0 1867.36  6344.5 1869.19
#Mann=3,-1,0
  4537.1    0.05       0  5006.5    0.05       0  5010.5    0.05       0
Bank Sta=5006.5,5010.5
Exp/Cntr=0.3,0.1

Type RM Length L Ch R = 1,6324,286,286,286
BEGIN DESCRIPTION:
Elm 01 95 6323.9
END DESCRIPTION:
XS GIS Cut Line= 4
      1609421.93      6798295.12      1609854.22      6798234.36
      1610212.76      6798196.87      1611090.77      6798046.69
#Sta/Elev= 30
  4562.7 1869.39  4579.5 1868.98  4767.8 1867.98  4828.4 1867.14  4858.7 1867.07
  4899.0 1867.71  4935.8 1866.18  4979.8 1865.71  4997.1 1864.38  5006.7 1864.27
  5006.9 1863.77  5010.4 1863.77  5010.7 1864.27  5013.7 1865.14  5020.1 1865.95
  5050.3 1866.69  5171.0 1865.35  5281.6 1865.14  5445.1 1865.96  5675.4 1866.30
  5740.5 1865.96  5795.5 1866.29  5960.6 1865.88  6143.2 1866.10  6183.8 1865.74
  6204.1 1866.10  6216.2 1866.86  6224.4 1866.25  6234.5 1866.57  6250.5 1867.90
#Mann=3,-1,0
  4562.7    0.05       0  5006.7    0.05       0  5010.7    0.05       0
Bank Sta=5006.7,5010.7
Exp/Cntr=0.3,0.1

Type RM Length L Ch R = 1,6038,459,459,459
BEGIN DESCRIPTION:
Elm 01 95 6038.09
END DESCRIPTION:
XS GIS Cut Line= 4
      1609460.11      6798696.17      1609960.12      6798489.57
      1610253.44      6798313.58      1611094.93      6798155.95
#Sta/Elev= 30
  4458.4 1870.72  4474.5 1871.23  4491.8 1869.80  4545.0 1868.50  4776.5 1866.90
  4799.1 1865.37  4842.4 1864.72  4859.1 1865.34  4864.5 1864.75  4874.8 1865.49
  4883.0 1866.98  4906.9 1865.58  4936.2 1865.88  4960.1 1864.57  4983.0 1864.37
  4997.3 1862.96  4997.6 1862.46  5001.1 1862.46  5001.3 1862.96  5027.1 1864.43
  5091.2 1865.96  5128.2 1865.24  5207.9 1865.63  5281.7 1864.68  5829.9 1864.50
  6055.5 1865.95  6108.1 1865.29  6160.7 1866.28  6167.2 1865.61  6197.6 1867.07
#Mann=3,-1,0
  4458.4    0.05       0  4997.3    0.05       0  5001.3    0.05       0
Bank Sta=4997.3,5001.3
Exp/Cntr=0.3,0.1

Type RM Length L Ch R = 1,5579,427,427,427
BEGIN DESCRIPTION:
Elm 01 95 5579.3
END DESCRIPTION:
XS GIS Cut Line= 4
      1609523.48      6799010.75      1610250.92      6798835.40
      1610574.86      6798715.72      1611105.40      6798583.02
#Sta/Elev= 30
  4254.0 1867.89  4326.1 1866.16  4348.1 1866.89  4373.1 1865.58  4399.6 1865.20
  4440.7 1865.55  4451.0 1865.20  4457.0 1864.34  4553.9 1864.56  4595.0 1863.70
  4629.7 1864.62  4666.5 1863.56  4739.0 1863.41  4797.4 1862.51  4903.6 1862.95
  4968.2 1861.20  4968.4 1860.70  4971.9 1860.70  4972.2 1861.20  4985.9 1862.00
  5005.7 1861.51  5071.4 1862.64  5198.5 1861.74  5732.0 1863.01  5801.3 1862.38
  5842.5 1863.51  5855.7 1863.30  5863.2 1862.56  5883.8 1864.06  5894.5 1864.18
#Mann=3,-1,0
  4254.0    0.05       0  4968.2    0.05       0  4972.2    0.05       0
Bank Sta=4968.2,4972.2
Exp/Cntr=0.3,0.1

Type RM Length L Ch R = 1,5152,415,415,415
BEGIN DESCRIPTION:
Elm 01 95 5152.32
END DESCRIPTION:
XS GIS Cut Line= 4
      1609589.94      6799330.54      1610352.14      6799231.58
      1610851.80      6799177.52      1611107.10      6799083.03
#Sta/Elev= 30
  4227.7 1861.58  4323.6 1862.23  4440.6 1861.45  4445.6 1861.75  4514.7 1861.40
  4525.2 1861.76  4636.2 1861.63  4847.9 1860.17  4979.0 1860.19  4989.7 1859.76
  4995.2 1858.69  5009.2 1858.60  5029.3 1859.64  5039.4 1859.37  5109.8 1859.66
  5180.2 1859.12  5258.8 1859.02  5290.9 1859.59  5355.6 1859.92  5651.1 1859.16
  5656.4 1859.36  5681.5 1858.78  5686.8 1859.05  5702.7 1858.50  5703.0 1858.00
  5706.8 1858.00  5707.1 1858.50  5726.2 1859.70  5742.3 1859.58  5771.1 1861.05
#Mann=3,-1,0
  4227.7    0.05       0  5702.7    0.05       0  5707.1    0.05       0
Bank Sta=5702.7,5707.1
Exp/Cntr=0.3,0.1

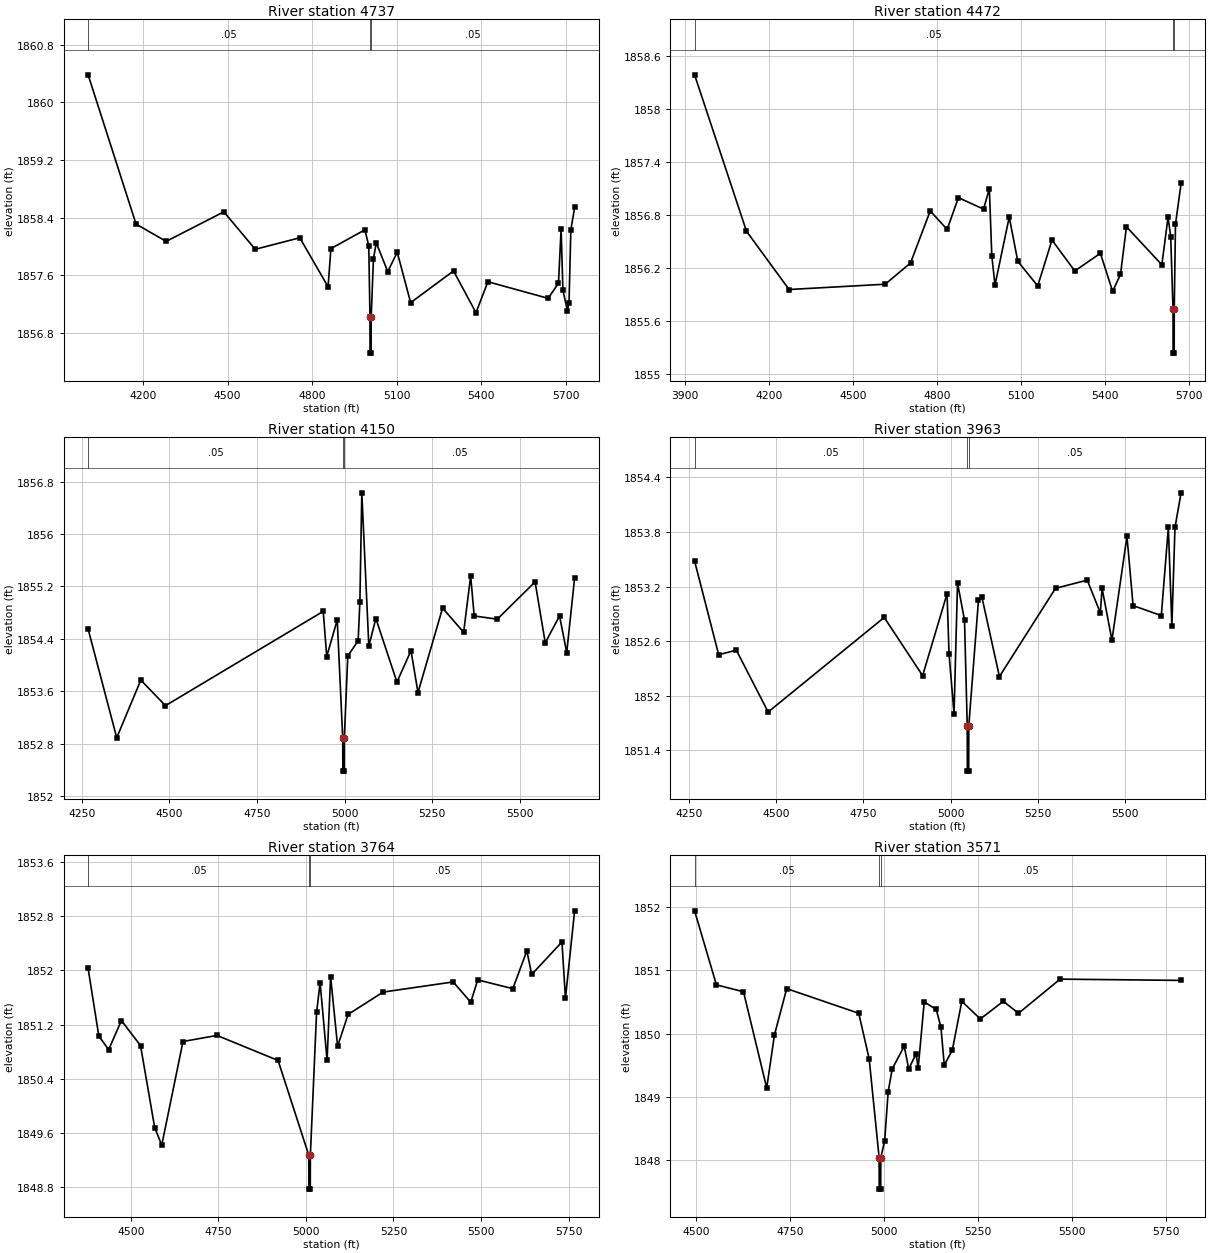
Type RM Length L Ch R = 1,4737,265,265,265
BEGIN DESCRIPTION:
Elm 01 95 4737.07
END DESCRIPTION:
XS GIS Cut Line= 5
      1609421.40      6799605.60      1609900.74      6799684.09
      1610408.71      6799630.42      1610946.50      6799534.57
      1611106.62      6799442.68
#Sta/Elev= 30
  4004.7 1860.38  4174.9 1858.31  4281.9 1858.07  4486.7 1858.48  4598.1 1857.96
  4756.2 1858.12  4856.7 1857.44  4866.8 1857.97  4987.4 1858.23  5001.2 1858.01
  5005.4 1857.02  5005.7 1856.52  5009.5 1856.52  5009.8 1857.02  5017.8 1857.83
  5027.9 1858.05  5068.6 1857.65  5102.3 1857.92  5149.8 1857.22  5302.2 1857.66
  5381.9 1857.08  5424.1 1857.51  5638.0 1857.28  5674.8 1857.49  5684.1 1858.24
  5690.6 1857.39  5706.4 1857.11  5712.2 1857.22  5718.7 1858.23  5732.1 1858.54
#Mann=3,-1,0
  4004.7    0.05       0  5005.4    0.05       0  5009.8    0.05       0
Bank Sta=5005.4,5009.8
Exp/Cntr=0.3,0.1

Type RM Length L Ch R = 1,4472,322,322,322
BEGIN DESCRIPTION:
Elm 01 95 4471.76
END DESCRIPTION:
XS GIS Cut Line= 5
      1609402.22      6799853.85      1609897.21      6799935.36
      1610457.55      6799880.16      1610883.13      6799801.59
      1611110.28      6799727.22
#Sta/Elev= 30
  3934.7 1858.39  4119.9 1856.62  4272.0 1855.96  4615.0 1856.02  4705.4 1856.26
  4775.8 1856.85  4836.1 1856.64  4876.3 1857.00  4966.1 1856.87  4986.8 1857.10
  4995.6 1856.34  5007.0 1856.01  5057.8 1856.78  5088.3 1856.28  5159.5 1856.00
  5210.4 1856.52  5291.7 1856.17  5383.2 1856.37  5426.7 1855.94  5454.9 1856.13
  5476.2 1856.67  5602.5 1856.24  5624.7 1856.78  5634.1 1856.56  5642.4 1855.74
  5642.7 1855.24  5646.5 1855.24  5646.8 1855.74  5651.2 1856.70  5671.2 1857.16
#Mann=3,-1,0
  3934.7    0.05       0  5642.4    0.05       0  5646.8    0.05       0
Bank Sta=5642.4,5646.8
Exp/Cntr=0.3,0.1

Type RM Length L Ch R = 1,4150,187,187,187
BEGIN DESCRIPTION:
Elm 01 95 4149.68
END DESCRIPTION:
XS GIS Cut Line= 5
      1609725.16      6800145.52      1610008.27      6800172.72
      1610455.81      6800156.20      1610891.53      6800123.93
      1611107.14      6800079.55
#Sta/Elev= 30
  4267.7 1854.55  4349.4 1852.89  4418.2 1853.77  4488.6 1853.38  4939.1 1854.82
  4949.1 1854.13  4979.1 1854.69  4994.8 1852.88  4995.2 1852.38  4999.0 1852.38
  4999.3 1852.88  5009.2 1854.14  5038.8 1854.37  5043.8 1854.97  5049.3 1856.63
  5069.3 1854.29  5089.4 1854.71  5149.6 1853.74  5189.7 1854.22  5209.7 1853.58
  5279.9 1854.87  5340.1 1854.50  5360.1 1855.36  5370.2 1854.75  5436.1 1854.70
  5544.1 1855.27  5573.1 1854.34  5614.0 1854.75  5634.4 1854.19  5657.0 1855.33
#Mann=3,-1,0
  4267.7    0.05       0  4994.8    0.05       0  4999.3    0.05       0
Bank Sta=4994.8,4999.3
Exp/Cntr=0.3,0.1

Type RM Length L Ch R = 1,3963,199,199,199
BEGIN DESCRIPTION:
Elm 01 95 3963.36
END DESCRIPTION:
XS GIS Cut Line= 5
      1609726.87      6800275.73      1610140.09      6800340.86
      1610451.33      6800342.55      1610685.22      6800340.96
      1611111.17      6800281.10
#Sta/Elev= 30
  4266.3 1853.48  4335.3 1852.45  4385.9 1852.50  4477.0 1851.82  4809.5 1852.86
  4919.5 1852.22  4989.5 1853.12  4995.2 1852.46  5009.5 1851.80  5019.5 1853.24
  5039.5 1852.83  5047.3 1851.67  5047.6 1851.17  5051.5 1851.17  5051.8 1851.67
  5079.5 1853.05  5089.5 1853.08  5139.5 1852.21  5300.2 1853.18  5391.1 1853.27
  5428.6 1852.91  5433.6 1853.18  5461.8 1852.61  5504.9 1853.75  5522.4 1852.99
  5603.2 1852.88  5623.4 1853.85  5633.5 1852.77  5642.4 1853.85  5659.9 1854.23
#Mann=3,-1,0
  4266.3    0.05       0  5047.3    0.05       0  5051.8    0.05       0
Bank Sta=5047.3,5051.8
Exp/Cntr=0.3,0.1

Type RM Length L Ch R = 1,3764,193,193,193
BEGIN DESCRIPTION:
Elm 01 95 3764.48
END DESCRIPTION:
XS GIS Cut Line= 5
      1609726.94      6800438.93      1610140.11      6800500.09
      1610345.71      6800497.70      1610667.87      6800502.47
      1611111.17      6800475.46
#Sta/Elev= 30
  4377.8 1852.03  4408.4 1851.03  4436.5 1850.83  4472.9 1851.26  4527.5 1850.89
  4567.9 1849.68  4588.1 1849.42  4648.8 1850.95  4745.9 1851.04  4920.4 1850.67
  5008.1 1849.27  5008.4 1848.77  5012.3 1848.77  5012.6 1849.27  5030.4 1851.38
  5040.4 1851.82  5060.4 1850.67  5070.4 1851.91  5090.4 1850.88  5120.4 1851.35
  5220.4 1851.68  5420.6 1851.83  5470.7 1851.53  5490.7 1851.86  5590.9 1851.73
  5631.0 1852.29  5644.7 1851.94  5731.2 1852.42  5741.2 1851.59  5767.4 1852.88
#Mann=3,-1,0
  4377.8    0.05       0  5008.1    0.05       0  5012.6    0.05       0
Bank Sta=5008.1,5012.6
Exp/Cntr=0.3,0.1

Type RM Length L Ch R = 1,3571,273,273,273
BEGIN DESCRIPTION:
Elm 01 95 3571.36
END DESCRIPTION:
XS GIS Cut Line= 5
      1609728.65      6800454.55      1610064.45      6800538.22
      1610203.77      6800611.20      1610460.77      6800706.46
      1610975.14      6800649.00
#Sta/Elev= 30
  4496.2 1851.94  4554.3 1850.77  4626.4 1850.66  4688.2 1849.14  4708.9 1849.98
  4741.4 1850.71  4933.2 1850.32  4960.9 1849.60  4987.4 1848.04  4987.7 1847.54
  4991.6 1847.54  4991.9 1848.04  5002.1 1848.30  5011.5 1849.08  5022.2 1849.44
  5054.2 1849.80  5066.2 1849.44  5085.9 1849.68  5091.3 1849.45  5107.5 1850.50
  5139.5 1850.38  5152.0 1850.10  5160.8 1849.50  5182.4 1849.74  5207.5 1850.51
  5256.8 1850.23  5318.1 1850.51  5358.4 1850.32  5469.1 1850.86  5791.2 1850.84
#Mann=3,-1,0
  4496.2    0.05       0  4987.4    0.05       0  4991.9    0.05       0
Bank Sta=4987.4,4991.9
Exp/Cntr=0.3,0.1

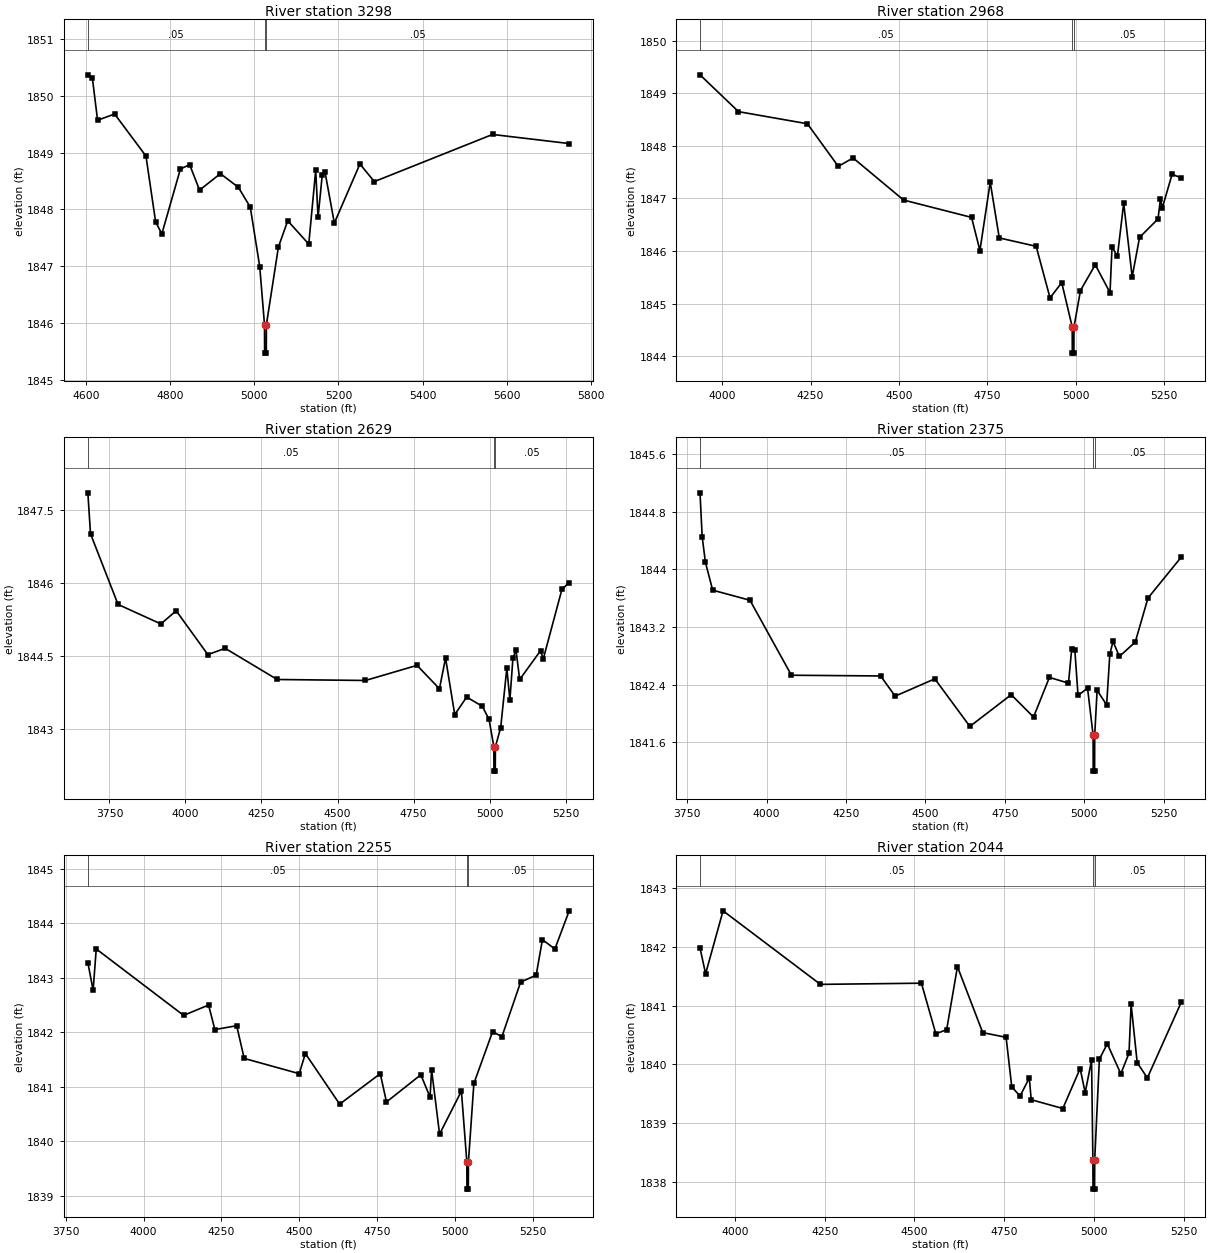
Type RM Length L Ch R = 1,3298,330,330,330
BEGIN DESCRIPTION:
Elm 01 95 3297.51
END DESCRIPTION:
XS GIS Cut Line= 5
      1609725.15      6800635.10      1609958.28      6800742.04
      1610061.97      6800835.80      1610321.69      6800969.81
      1610777.26      6800978.86
#Sta/Elev= 30
  4604.3 1850.37  4615.1 1850.31  4627.4 1849.57  4667.9 1849.68  4742.4 1848.94
  4765.4 1847.78  4780.2 1847.57  4824.2 1848.71  4846.2 1848.79  4869.8 1848.34
  4919.4 1848.63  4962.0 1848.39  4990.4 1848.04  5012.9 1846.99  5024.2 1845.97
  5024.5 1845.47  5028.4 1845.47  5028.7 1845.97  5057.3 1847.34  5079.4 1847.80
  5129.4 1847.39  5145.9 1848.69  5151.5 1847.86  5161.5 1848.61  5168.0 1848.66
  5190.2 1847.76  5251.0 1848.80  5285.3 1848.49  5566.2 1849.32  5748.5 1849.16
#Mann=3,-1,0
  4604.3    0.05       0  5024.2    0.05       0  5028.7    0.05       0
Bank Sta=5024.2,5028.7
Exp/Cntr=0.3,0.1

Type RM Length L Ch R = 1,2968,339,339,339
BEGIN DESCRIPTION:
Elm 01 95 2968.43
END DESCRIPTION:
XS GIS Cut Line= 4
      1608964.72      6800742.73      1609730.10      6801066.59
      1609954.29      6801133.72      1610238.16      6801219.66
#Sta/Elev= 30
  3937.2 1849.35  4046.1 1848.65  4241.0 1848.42  4328.4 1847.61  4370.3 1847.77
  4513.0 1846.97  4705.4 1846.64  4729.1 1846.01  4758.2 1847.31  4783.8 1846.25
  4888.2 1846.09  4927.4 1845.11  4960.5 1845.40  4990.1 1844.56  4990.5 1844.06
  4994.8 1844.06  4995.2 1844.56  5013.5 1845.25  5055.3 1845.74  5097.1 1845.21
  5102.8 1846.08  5118.0 1845.90  5135.8 1846.91  5159.8 1845.51  5180.7 1846.26
  5232.9 1846.61  5239.8 1846.99  5245.0 1846.82  5272.7 1847.46  5298.9 1847.39
#Mann=3,-1,0
  3937.2    0.05       0  4990.1    0.05       0  4995.2    0.05       0
Bank Sta=4990.1,4995.2
Exp/Cntr=0.3,0.1

Type RM Length L Ch R = 1,2629,254,254,254
BEGIN DESCRIPTION:
Elm 01 95 2629.24
END DESCRIPTION:
XS GIS Cut Line= 4
      1608546.40      6801287.89      1609502.82      6801398.33
      1609857.02      6801441.40      1610118.77      6801472.66
#Sta/Elev= 30
  3678.9 1847.85  3687.6 1847.01  3778.2 1845.56  3919.1 1845.16  3969.4 1845.43
  4073.6 1844.53  4130.5 1844.66  4301.6 1844.02  4591.9 1844.00  4761.5 1844.31
  4835.3 1843.83  4855.4 1844.46  4885.6 1843.30  4924.9 1843.66  4976.3 1843.47
  4998.5 1843.20  5014.2 1842.64  5014.6 1842.14  5018.9 1842.14  5019.3 1842.64
  5036.7 1843.03  5056.9 1844.25  5067.0 1843.60  5077.0 1844.46  5087.1 1844.62
  5099.2 1844.02  5167.7 1844.61  5176.7 1844.44  5238.2 1845.87  5262.1 1846.01
#Mann=3,-1,0
  3678.9    0.05       0  5014.2    0.05       0  5019.3    0.05       0
Bank Sta=5014.2,5019.3
Exp/Cntr=0.3,0.1

Type RM Length L Ch R = 1,2375,120,120,120
BEGIN DESCRIPTION:
Elm 01 95 2374.95
END DESCRIPTION:
XS GIS Cut Line= 4
      1608548.13      6801600.39      1609447.37      6801662.93
      1609755.12      6801658.85      1610060.03      6801658.85
#Sta/Elev= 30
  3790.8 1845.06  3797.7 1844.45  3807.7 1844.10  3830.6 1843.71  3948.0 1843.57
  4078.4 1842.53  4359.0 1842.52  4404.6 1842.24  4529.4 1842.48  4639.7 1841.82
  4769.8 1842.26  4839.9 1841.95  4889.9 1842.50  4949.9 1842.42  4959.9 1842.89
  4969.9 1842.88  4979.9 1842.25  5009.9 1842.35  5027.3 1841.70  5027.7 1841.20
  5032.0 1841.20  5032.4 1841.70  5039.9 1842.32  5069.9 1842.12  5079.9 1842.82
  5089.9 1843.00  5109.9 1842.79  5159.9 1842.99  5199.9 1843.60  5304.9 1844.17
#Mann=3,-1,0
  3790.8    0.05       0  5027.3    0.05       0  5032.4    0.05       0
Bank Sta=5027.3,5032.4
Exp/Cntr=0.3,0.1

Type RM Length L Ch R = 1,2255,211,211,211
BEGIN DESCRIPTION:
Elm 01 95 2255.2
END DESCRIPTION:
XS GIS Cut Line= 4
      1608548.10      6801734.07      1609444.02      6801785.92
      1609724.74      6801768.23      1610091.01      6801773.42
#Sta/Elev= 30
  3821.4 1843.28  3838.3 1842.77  3848.3 1843.53  4128.8 1842.31  4208.9 1842.50
  4229.0 1842.05  4299.1 1842.12  4323.2 1841.52  4499.8 1841.24  4519.5 1841.61
  4629.6 1840.68  4759.9 1841.24  4779.9 1840.72  4890.1 1841.22  4919.7 1840.81
  4924.7 1841.31  4950.3 1840.13  5020.4 1840.92  5037.8 1839.62  5038.2 1839.12
  5042.5 1839.12  5042.9 1839.62  5060.4 1841.06  5120.4 1842.01  5150.4 1841.92
  5210.4 1842.92  5260.4 1843.05  5280.4 1843.70  5320.4 1843.53  5366.4 1844.23
#Mann=3,-1,0
  3821.4    0.05       0  5037.8    0.05       0  5042.9    0.05       0
Bank Sta=5037.8,5042.9
Exp/Cntr=0.3,0.1

Type RM Length L Ch R = 1,2044,247,247,247
BEGIN DESCRIPTION:
Elm 01 95 2043.63
END DESCRIPTION:
XS GIS Cut Line= 4
      1608541.11      6801761.84      1609396.96      6801843.70
      1609621.87      6801921.87      1609841.60      6802025.27
#Sta/Elev= 30
  3902.7 1841.98  3918.3 1841.54  3966.9 1842.61  4238.1 1841.36  4519.4 1841.38
  4559.6 1840.52  4589.7 1840.59  4619.8 1841.66  4690.2 1840.54  4755.3 1840.46
  4771.0 1839.62  4794.1 1839.46  4819.9 1839.77  4825.2 1839.40  4913.3 1839.25
  4961.5 1839.93  4975.5 1839.52  4993.3 1840.07  4997.0 1838.38  4997.4 1837.88
  5001.7 1837.88  5002.1 1838.38  5015.1 1840.09  5037.2 1840.35  5074.8 1839.84
  5097.6 1840.19  5103.5 1841.02  5120.4 1840.03  5148.7 1839.77  5243.4 1841.06
#Mann=3,-1,0
  3902.7    0.05       0  4997.0    0.05       0  5002.1    0.05       0
Bank Sta=4997,5002.1
Exp/Cntr=0.3,0.1

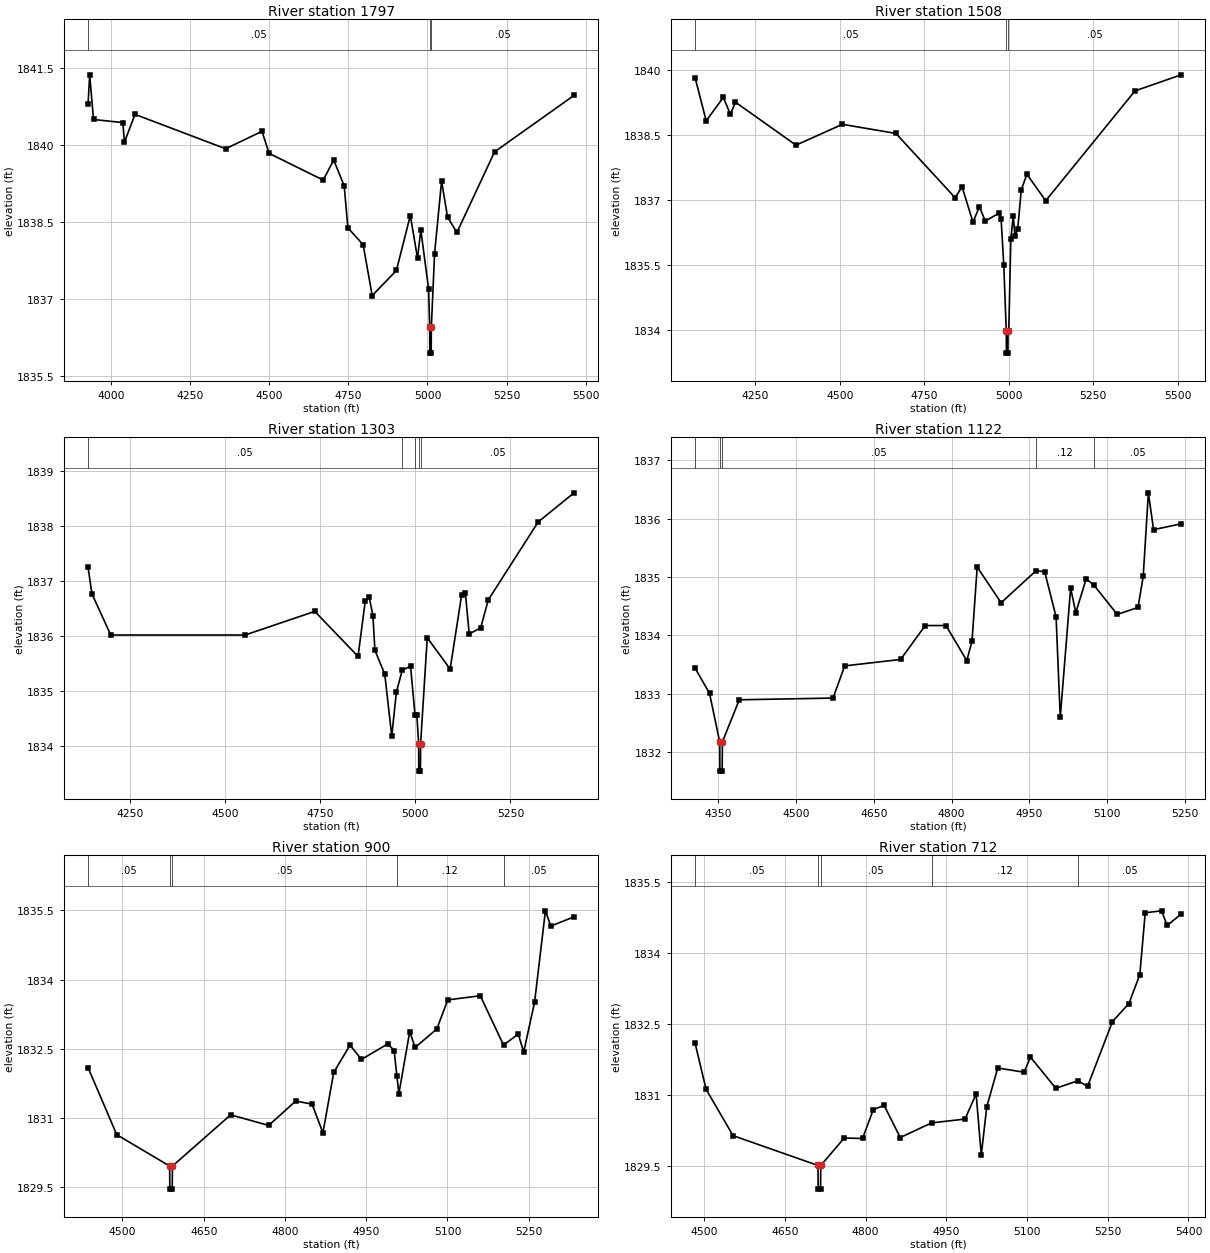
Type RM Length L Ch R = 1,1797,289,289,289
BEGIN DESCRIPTION:
Elm 01 95 1797.25
END DESCRIPTION:
XS GIS Cut Line= 5
      1608498.61      6801790.49      1609301.29      6802030.09
      1609514.93      6802128.51      1609657.44      6802185.75
      1609966.06      6802187.62
#Sta/Elev= 30
  3928.0 1840.81  3933.1 1841.37  3945.1 1840.50  4037.7 1840.44  4043.0 1840.06
  4076.1 1840.60  4362.5 1839.93  4477.3 1840.27  4499.8 1839.84  4670.7 1839.32
  4703.8 1839.71  4736.9 1839.21  4748.7 1838.39  4796.9 1838.06  4825.4 1837.07
  4901.9 1837.56  4945.9 1838.63  4968.6 1837.80  4979.0 1838.35  5003.6 1837.20
  5007.1 1836.45  5007.4 1835.95  5011.8 1835.95  5012.2 1836.45  5022.5 1837.89
  5044.6 1839.30  5063.4 1838.60  5093.0 1838.30  5212.0 1839.87  5463.1 1840.97
#Mann=3,-1,0
  3928.0    0.05       0  5007.1    0.05       0  5012.2    0.05       0
Bank Sta=5007.1,5012.2
Exp/Cntr=0.3,0.1

Type RM Length L Ch R = 1,1508,205,205,205
BEGIN DESCRIPTION:
Elm 01 95 1508.39
END DESCRIPTION:
XS GIS Cut Line= 5
      1608502.56      6801834.79      1609086.81      6802237.20
      1609299.21      6802289.10      1609510.84      6802344.53
      1609800.99      6802319.22
#Sta/Elev= 30
  4072.2 1839.81  4104.9 1838.82  4155.6 1839.36  4176.6 1838.97  4191.5 1839.25
  4370.7 1838.26  4508.0 1838.74  4666.3 1838.53  4841.5 1837.05  4862.1 1837.30
  4894.2 1836.49  4913.6 1836.84  4930.7 1836.51  4972.4 1836.70  4977.5 1836.57
  4985.6 1835.49  4992.9 1833.97  4993.3 1833.47  4997.7 1833.47  4998.1 1833.97
  5000.3 1833.97  5006.3 1836.09  5013.5 1836.63  5018.7 1836.16  5026.9 1836.34
  5037.3 1837.23  5054.0 1837.59  5109.6 1836.98  5373.8 1839.51  5510.3 1839.88
#Mann=3,-1,0
  4072.2    0.05       0  4992.9    0.05       0  4998.1    0.05       0
Bank Sta=4992.9,4998.1
Exp/Cntr=0.3,0.1

Type RM Length L Ch R = 1,1303,181,181,181
BEGIN DESCRIPTION:
Elm 01 95 1302.71
END DESCRIPTION:
XS GIS Cut Line= 5
      1608503.84      6802024.89      1608870.85      6802394.08
      1609205.54      6802465.68      1609410.27      6802483.55
      1609619.68      6802463.67
#Sta/Elev= 30
  4138.8 1837.25  4148.9 1836.77  4198.4 1836.02  4552.0 1836.02  4735.2 1836.45
  4849.1 1835.63  4868.1 1836.64  4878.4 1836.71  4888.3 1836.37  4893.5 1835.74
  4919.3 1835.31  4937.8 1834.18  4950.0 1834.98  4965.5 1835.38  4987.3 1835.45
  4999.0 1834.56  5003.9 1834.56  5008.5 1834.04  5008.9 1833.54  5013.3 1833.54
  5013.7 1834.04  5031.2 1835.97  5091.4 1835.40  5121.5 1836.74  5131.6 1836.78
  5141.6 1836.04  5171.7 1836.15  5191.8 1836.66  5323.1 1838.08  5417.5 1838.61
#Mann=5,-1,0
  4138.8    0.05       0  4965.5    0.12       0  4999.0    0.05       0
  5008.5    0.05       0  5013.7    0.05       0
Bank Sta=5008.5,5013.7
Exp/Cntr=0.3,0.1

Type RM Length L Ch R = 1,1122,222,222,222
BEGIN DESCRIPTION:
Elm 01 95 1122.48
END DESCRIPTION:
XS GIS Cut Line= 4
      1608499.94      6802437.64      1608855.25      6802608.70
      1609156.93      6802630.61      1609398.22      6802637.55
#Sta/Elev= 30
  4305.0 1833.44  4332.8 1833.01  4352.4 1832.18  4352.8 1831.68  4357.2 1831.68
  4357.6 1832.18  4390.2 1832.90  4571.2 1832.93  4593.8 1833.48  4701.7 1833.59
  4749.2 1834.17  4789.3 1834.17  4829.4 1833.57  4839.5 1833.90  4849.5 1835.17
  4895.7 1834.56  4963.4 1835.11  4979.8 1835.09  5001.8 1834.32  5009.9 1832.60
  5029.9 1834.81  5039.9 1834.39  5059.9 1834.97  5075.0 1834.86  5119.9 1834.36
  5160.0 1834.48  5170.0 1835.01  5180.0 1836.44  5190.0 1835.81  5243.2 1835.91
#Mann=5,-1,0
  4305.0    0.05       0  4352.4    0.07       0  4357.6    0.05       0
  4963.4    0.12       0  5075.0    0.05       0
Bank Sta=4352.4,4357.6
Exp/Cntr=0.3,0.1

Type RM Length L Ch R = 1,900,188,188,188
BEGIN DESCRIPTION:
Elm 01 95 899.92
END DESCRIPTION:
XS GIS Cut Line= 3
      1608492.12      6802786.58      1609056.23      6802816.37
      1609387.78      6802795.54
#Sta/Elev= 30
  4436.6 1832.09  4489.5 1830.64  4587.1 1829.96  4587.5 1829.46  4591.9 1829.46
  4592.3 1829.96  4699.8 1831.07  4769.9 1830.84  4820.0 1831.37  4850.1 1831.30
  4870.1 1830.68  4890.1 1831.99  4920.1 1832.58  4941.3 1832.27  4990.2 1832.61
  5001.5 1832.46  5006.6 1831.92  5010.3 1831.53  5030.3 1832.87  5040.3 1832.53
  5080.4 1832.93  5100.5 1833.56  5160.6 1833.65  5203.5 1832.58  5230.7 1832.82
  5240.7 1832.43  5260.8 1833.51  5280.8 1835.49  5290.8 1835.16  5333.7 1835.36
#Mann=5,-1,0
  4436.6    0.05       0  4587.1    0.05       0  4592.3    0.05       0
  5006.6    0.12       0  5203.5    0.05       0
Bank Sta=4587.1,4592.3
Exp/Cntr=0.3,0.1

Type RM Length L Ch R = 1,712,233,233,233
BEGIN DESCRIPTION:
Elm 01 95 711.72
END DESCRIPTION:
XS GIS Cut Line= 3
      1608494.71      6802953.25      1609011.09      6802989.99
      1609390.64      6802922.40
#Sta/Elev= 30
  4483.1 1832.10  4503.4 1831.13  4553.6 1830.15  4711.4 1829.52  4711.8 1829.02
  4716.2 1829.02  4716.6 1829.52  4760.2 1830.10  4794.2 1830.09  4814.2 1830.70
  4834.3 1830.79  4864.3 1830.11  4922.6 1830.42  4984.6 1830.50  5005.3 1831.03
  5014.9 1829.74  5025.1 1830.76  5045.5 1831.58  5094.4 1831.49  5106.3 1831.81
  5153.4 1831.15  5194.6 1831.31  5212.4 1831.19  5258.7 1832.56  5289.2 1832.94
  5309.5 1833.55  5319.6 1834.86  5350.1 1834.90  5360.3 1834.59  5386.3 1834.83
#Mann=5,-1,0
  4483.1    0.05       0  4711.4    0.07       0  4716.6    0.05       0
  4922.6    0.12       0  5194.6    0.05       0
Bank Sta=4711.4,4716.6
Exp/Cntr=0.3,0.1