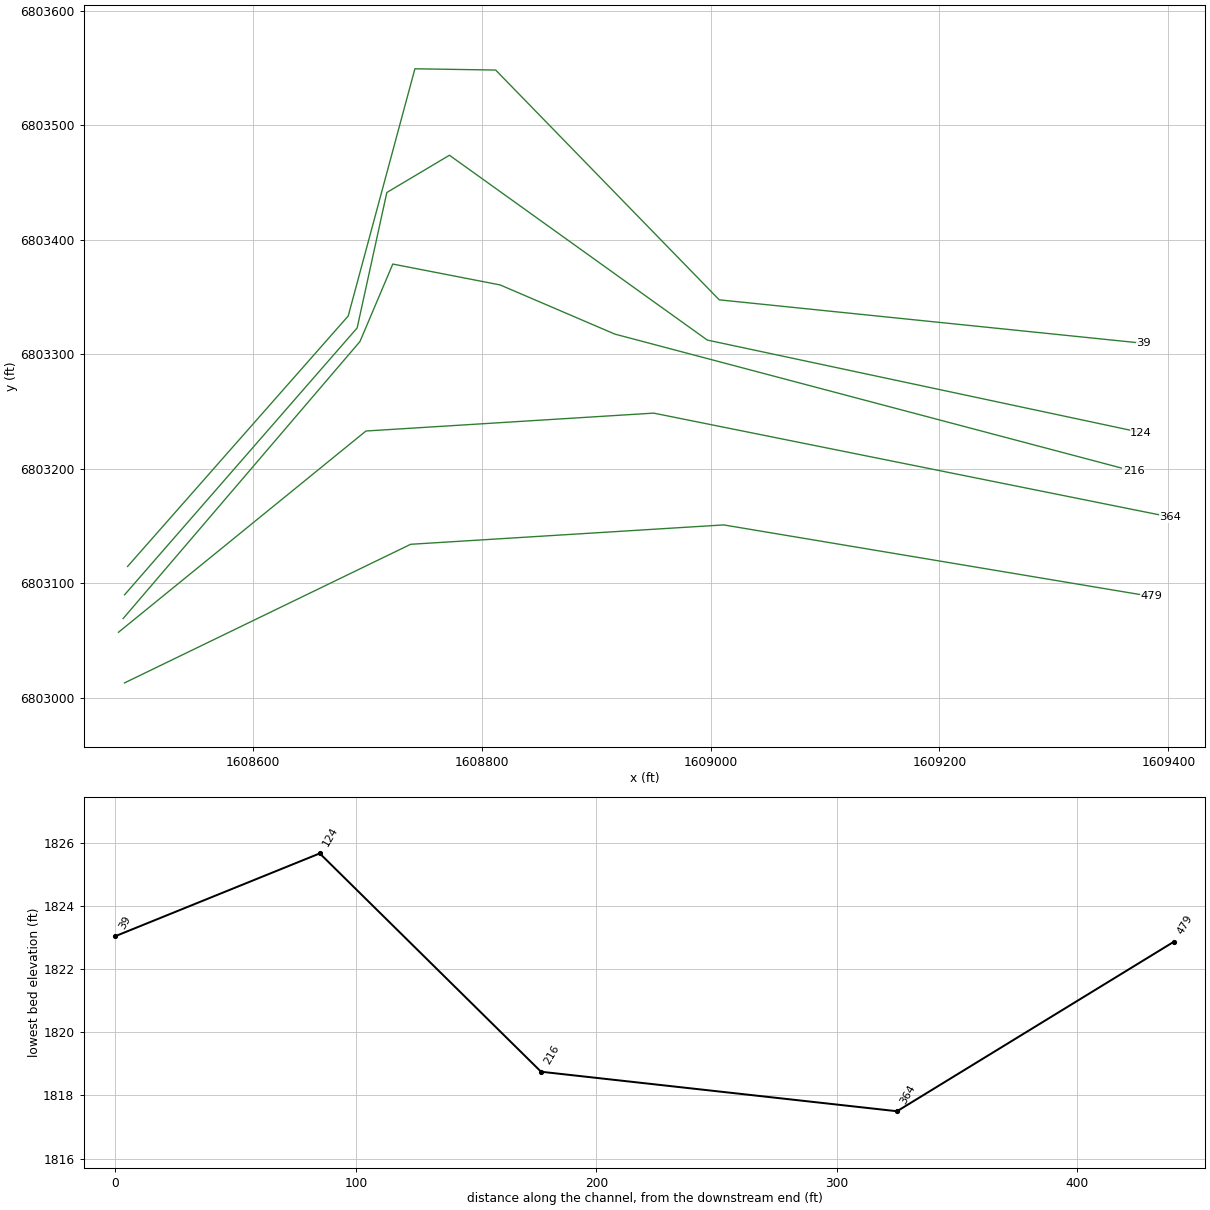
HEC-RAS study Elm 01 95.prj: Elm 01 95 Base Level Engineering

--- Elm 01 95.g01 (geometry) --- (continued)

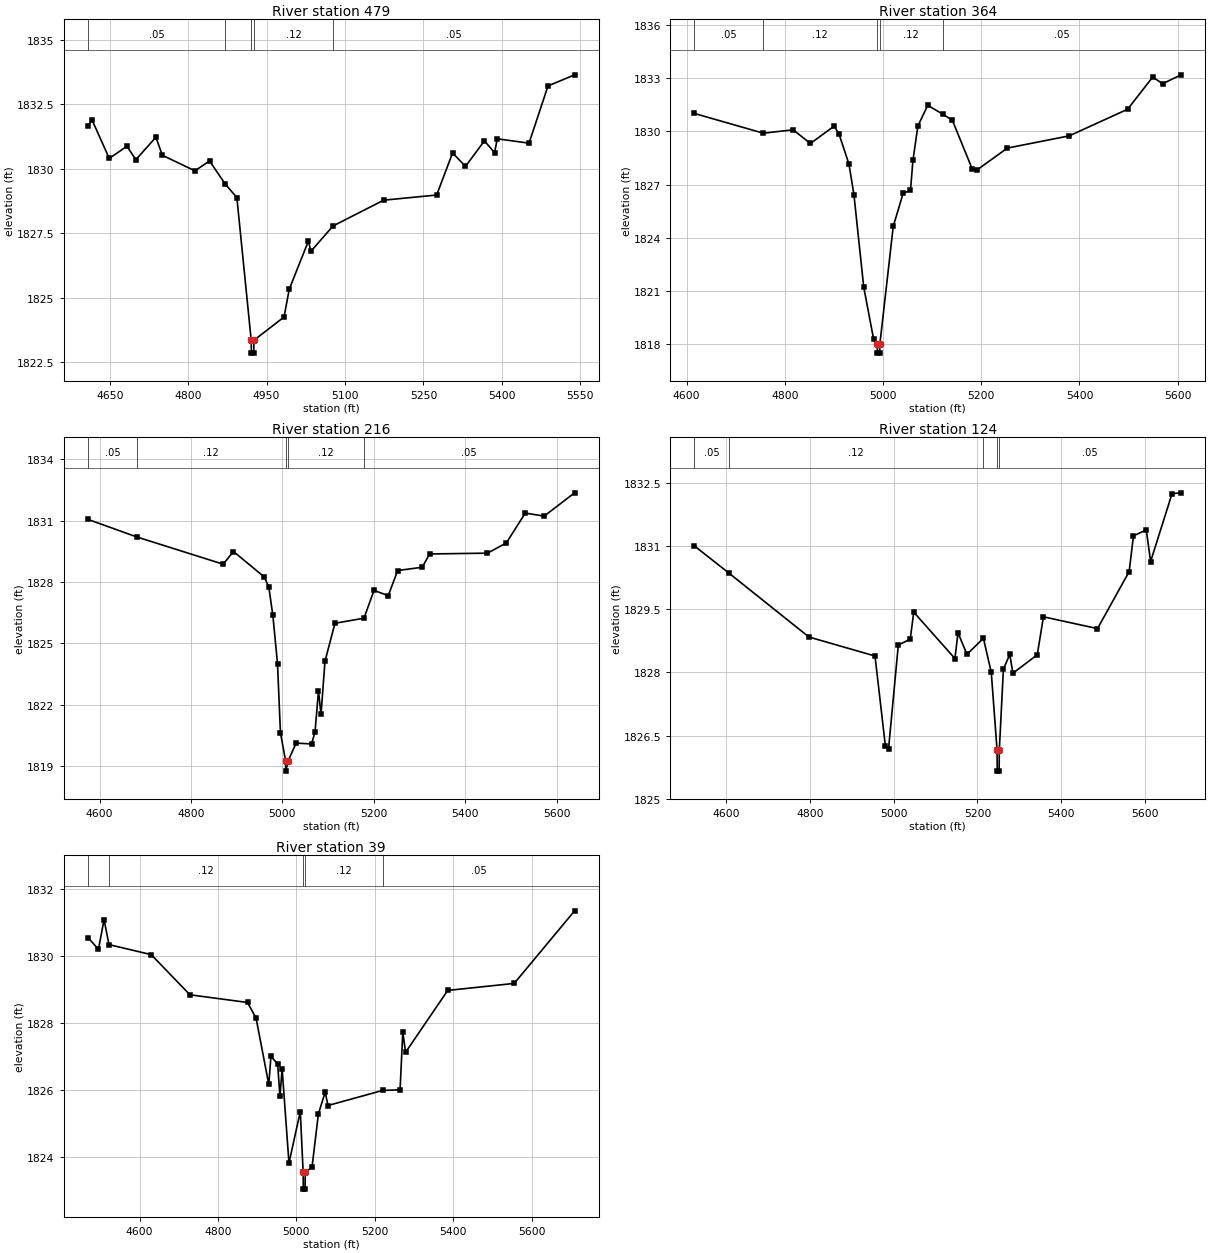
Type RM Length L Ch R = 1,479,115,115,115
BEGIN DESCRIPTION:
Mapping XS 69ac6b96
END DESCRIPTION:
XS GIS Cut Line= 4
      1608488.08      6803012.94      1608738.08      6803134.04
      1609011.51      6803150.96      1609385.18      6803088.47
#Sta/Elev= 30
  4608.5 1831.67  4616.2 1831.90  4649.2 1830.41  4682.9 1830.88  4700.0 1830.36
  4738.4 1831.23  4750.7 1830.53  4812.9 1829.93  4841.0 1830.31  4870.4 1829.43
  4893.2 1828.89  4920.6 1823.36  4921.0 1822.86  4925.5 1822.86  4925.9 1823.36
  4983.4 1824.26  4993.4 1825.34  5029.9 1827.20  5034.9 1826.81  5077.1 1827.79
  5173.9 1828.79  5275.3 1828.99  5305.7 1830.62  5330.4 1830.10  5366.6 1831.09
  5386.1 1830.63  5391.1 1831.17  5451.9 1831.00  5488.2 1833.22  5539.1 1833.65
#Mann=5,-1,0
  4608.5    0.05       0  4870.4    0.12       0  4920.6    0.07       0
  4925.9    0.12       0  5077.1    0.05       0
Bank Sta=4920.6,4925.9
Exp/Cntr=0.3,0.1

Type RM Length L Ch R = 1,364,148,148,148
BEGIN DESCRIPTION:
Mapping XS e60e6f51
END DESCRIPTION:
XS GIS Cut Line= 4
      1608482.85      6803057.20      1608699.01      6803232.99
      1608950.32      6803248.62      1609401.77      6803157.81
#Sta/Elev= 30
  4616.0 1831.01  4756.2 1829.90  4817.0 1830.09  4852.1 1829.32  4900.6 1830.30
  4910.6 1829.83  4930.7 1828.15  4940.7 1826.43  4960.7 1821.22  4980.8 1818.29
  4988.1 1818.00  4988.5 1817.50  4993.0 1817.50  4993.5 1818.00  5020.8 1824.65
  5040.9 1826.51  5055.9 1826.67  5060.9 1828.37  5070.9 1830.30  5091.0 1831.47
  5121.8 1830.97  5141.1 1830.63  5181.8 1827.87  5192.0 1827.84  5253.2 1829.06
  5379.2 1829.75  5498.0 1831.25  5549.0 1833.06  5569.4 1832.69  5606.9 1833.19
#Mann=5,-1,0
  4616.0    0.05       0  4756.2    0.12       0  4988.1    0.07       0
  4993.5    0.12       0  5121.8    0.05       0
Bank Sta=4988.1,4993.5
Exp/Cntr=0.3,0.1

Type RM Length L Ch R = 1,216,92,92,92
BEGIN DESCRIPTION:
Mapping XS 98703cce
END DESCRIPTION:
XS GIS Cut Line= 6
      1608486.91      6803069.16      1608693.79      6803311.18
      1608722.45      6803378.83      1608816.20      6803360.60
      1608916.46      6803317.63      1609369.55      6803197.85
#Sta/Elev= 30
  4574.5 1831.06  4681.6 1830.20  4870.3 1828.87  4892.9 1829.49  4960.1 1828.25
  4970.2 1827.76  4979.1 1826.37  4989.3 1824.00  4995.7 1820.63  5007.0 1819.25
  5007.5 1818.75  5012.4 1819.25  5030.1 1820.12  5063.9 1820.08  5071.4 1820.67
  5079.0 1822.68  5084.5 1821.52  5093.2 1824.12  5115.0 1825.98  5178.6 1826.23
  5200.5 1827.59  5231.7 1827.33  5252.3 1828.56  5306.1 1828.72  5322.2 1829.37
  5448.9 1829.41  5490.2 1829.91  5531.6 1831.37  5572.9 1831.22  5639.6 1832.36
#Mann=5,-1,0
  4574.5    0.05       0  4681.6    0.12       0  5007.0    0.07       0
  5012.4    0.12       0  5178.6    0.05       0
Bank Sta=5007,5012.4
Exp/Cntr=0.3,0.1

Type RM Length L Ch R = 1,124,85,85,85
BEGIN DESCRIPTION:
Mapping XS efff86d2
END DESCRIPTION:
XS GIS Cut Line= 6
      1608488.17      6803089.94      1608691.32      6803323.04
      1608717.24      6803441.33      1608771.93      6803473.88
      1608997.19      6803312.42      1609376.14      6803231.68
#Sta/Elev= 30
  4525.1 1831.00  4608.1 1830.35  4798.2 1828.84  4955.7 1828.39  4980.4 1826.26
  4988.0 1826.19  5011.3 1828.65  5039.7 1828.79  5048.1 1829.43  5146.3 1828.33
  5153.6 1828.94  5175.0 1828.43  5214.3 1828.81  5233.0 1828.00  5246.8 1826.16
  5247.2 1825.66  5251.7 1825.66  5252.2 1826.16  5261.9 1828.08  5277.2 1828.43
  5284.5 1827.98  5342.7 1828.42  5357.4 1829.32  5486.3 1829.04  5561.8 1830.39
  5572.1 1831.24  5602.7 1831.38  5613.0 1830.63  5664.1 1832.24  5685.7 1832.26
#Mann=5,-1,0
  4525.1    0.05       0  4608.1    0.12       0  5214.3    0.05       0
  5246.8    0.07       0  5252.2    0.05       0
Bank Sta=5246.8,5252.2
Exp/Cntr=0.3,0.1

Type RM Length L Ch R = 1,39,0,0,0
BEGIN DESCRIPTION:
Elm 01 95 2905.597
END DESCRIPTION:
XS GIS Cut Line= 6
      1608490.79      6803114.69      1608683.51      6803333.46
      1608741.77      6803549.40      1608812.30      6803548.31
      1609007.61      6803347.58      1609378.38      6803309.60
#Sta/Elev= 30
  4468.1 1830.56  4494.8 1830.21  4509.1 1831.10  4521.6 1830.35  4629.5 1830.05
  4728.2 1828.85  4875.2 1828.62  4897.1 1828.15  4929.5 1826.17  4935.0 1827.01
  4952.1 1826.78  4958.0 1825.81  4963.5 1826.64  4981.0 1823.82  5009.9 1825.36
  5017.2 1823.54  5017.7 1823.04  5022.2 1823.04  5022.6 1823.54  5039.9 1823.70
  5056.1 1825.29  5073.4 1825.94  5080.6 1825.54  5219.8 1825.99  5264.5 1826.01
  5271.5 1827.73  5278.6 1827.13  5386.1 1828.98  5555.8 1829.19  5710.0 1831.36
#Mann=5,-1,0
  4468.1    0.05       0  4521.6    0.12       0  5017.2    0.07       0
  5022.6    0.12       0  5219.8    0.05       0
Bank Sta=5017.2,5022.6
Exp/Cntr=0.3,0.1

Chan Stop Cuts=-1