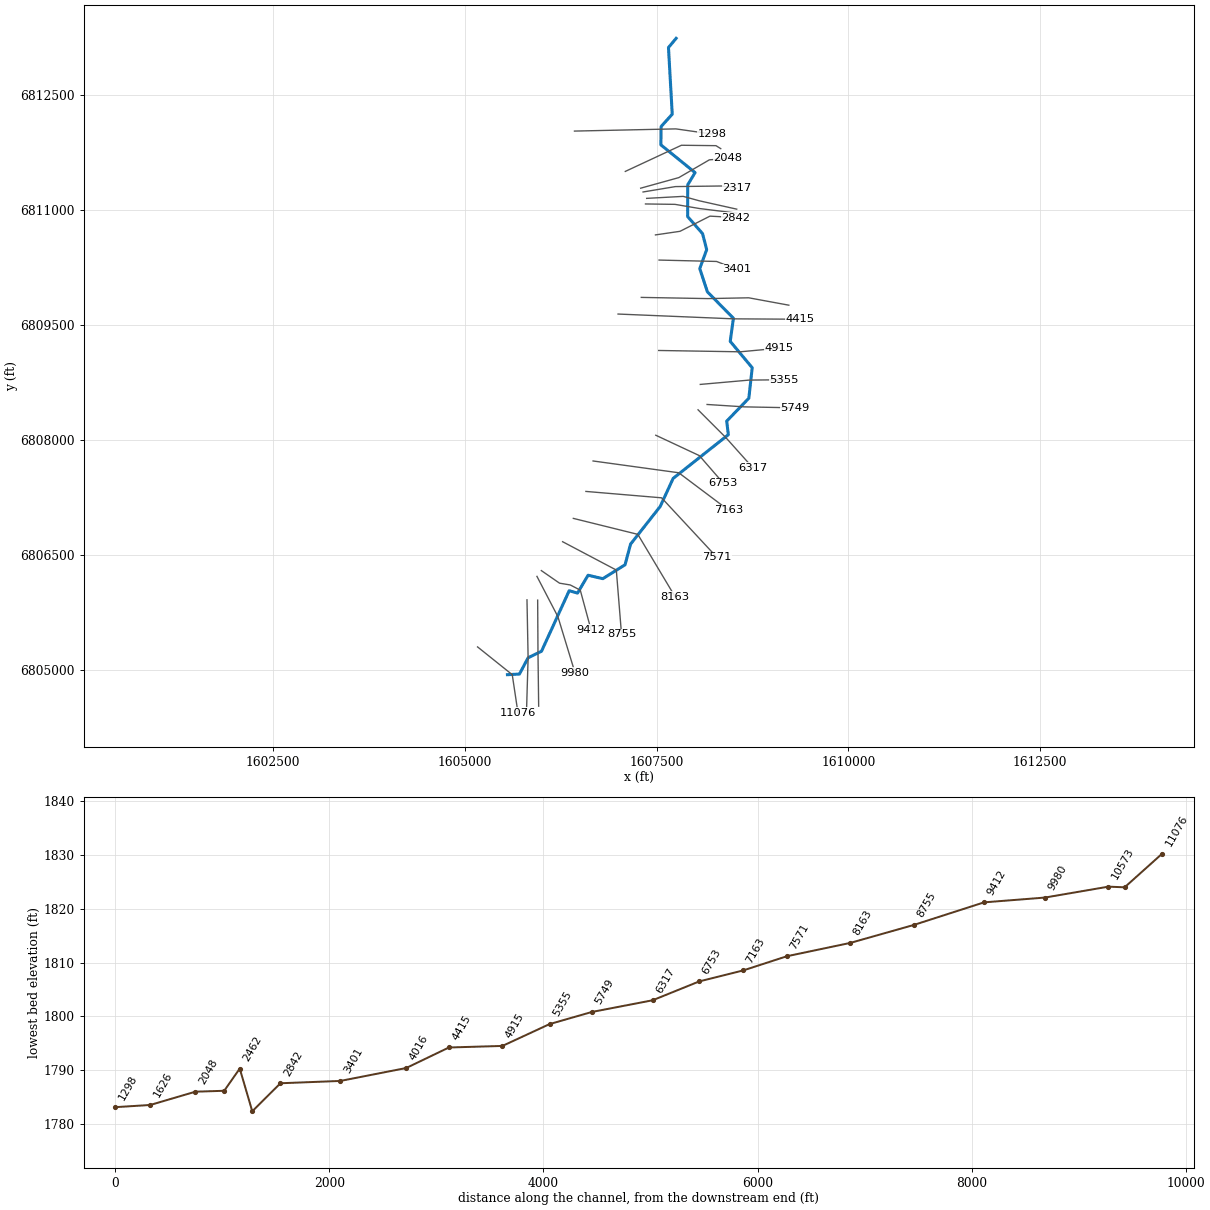
--- Elm 01 96.prj (project) ---

Proj Title=Elm 01 96 Base Level Engineering
Current Plan=p01
Default Exp/Contr=0.3,0.1
English Units
Geom File=g01
Flow File=f01
Plan File=p01
BEGIN DESCRIPTION:
Elm 01 96
END DESCRIPTION:

--- Elm 01 96.p01 (plan) ---

Plan Title=Multiple Run
Short Identifier=Multiple
Geom File=g01
Flow File=f01
Subcritical Flow
K Sum by GR= 0
Std Step Tol= 0.01
Critical Tol= 0.01
Num of Std Step Trials= 20
Max Error Tol= 0.3
Flow Tol Ratio= 0.001
Split Flow NTrial= 30
Split Flow Tol= 0.02
Split Flow Ratio= 0.02
Log Output Level= 0
Friction Slope Method= 1
Unsteady Friction Slope Method= 2
Unsteady Bridges Friction Slope Method= 1
Parabolic Critical Depth
Global Vel Dist=  1 , 1 , 1
Global Log Level= 0
CheckData=True
Encroach Param= -1, 0, 0, 0
BEGIN DESCRIPTION:
Multiple Run
END DESCRIPTION:

--- Elm 01 96.f01 (steady flow) ---

Flow Title=Multiple
Number of Profiles=7
Profile Names=10-year,25-year,50-year,1pct_min,100-year,1pct_plu,500-year
River Rch & RM= Elm 01 96,Reach-1,11076
     211     288     352     266     427     587     636
Boundary for River Rch & Prof#=Elm 01 96,Reach-1,1
Up Type=0
Dn Type=3
Dn Slope=0.001
Boundary for River Rch & Prof#=Elm 01 96,Reach-1,2
Up Type=0
Dn Type=3
Dn Slope=0.001
Boundary for River Rch & Prof#=Elm 01 96,Reach-1,3
Up Type=0
Dn Type=3
Dn Slope=0.001
Boundary for River Rch & Prof#=Elm 01 96,Reach-1,4
Up Type=0
Dn Type=3
Dn Slope=0.001
Boundary for River Rch & Prof#=Elm 01 96,Reach-1,5
Up Type=0
Dn Type=3
Dn Slope=0.001
Boundary for River Rch & Prof#=Elm 01 96,Reach-1,6
Up Type=0
Dn Type=3
Dn Slope=0.001
Boundary for River Rch & Prof#=Elm 01 96,Reach-1,7
Up Type=0
Dn Type=3
Dn Slope=0.001

--- Elm 01 96.g01 (geometry) ---

Geom Title=Existing Conditions

River Reach=Elm 01 96,Reach-1
Reach XY= 30
      1605555.00      6804938.00      1605711.22      6804945.78
      1605824.47      6805158.54      1605999.39      6805243.59
      1606360.26      6806033.34      1606468.39      6806001.54
      1606606.39      6806234.97      1606799.03      6806190.14
      1607088.51      6806370.95      1607160.48      6806640.44
      1607547.14      6807131.83      1607715.76      6807497.68
      1608435.63      6808068.00      1608414.29      6808244.67
      1608703.16      6808544.12      1608746.96      6808941.32
      1608460.45      6809285.55      1608501.63      6809586.72
      1608162.69      6809931.52      1608062.81      6810234.59
      1608153.18      6810481.88      1608099.53      6810690.45
      1607904.70      6810912.88      1607906.06      6811327.56
      1608001.90      6811486.35      1607556.05      6811848.43
      1607558.54      6812086.54      1607703.95      6812248.43
      1607654.95      6813118.02      1607755.00      6813238.00

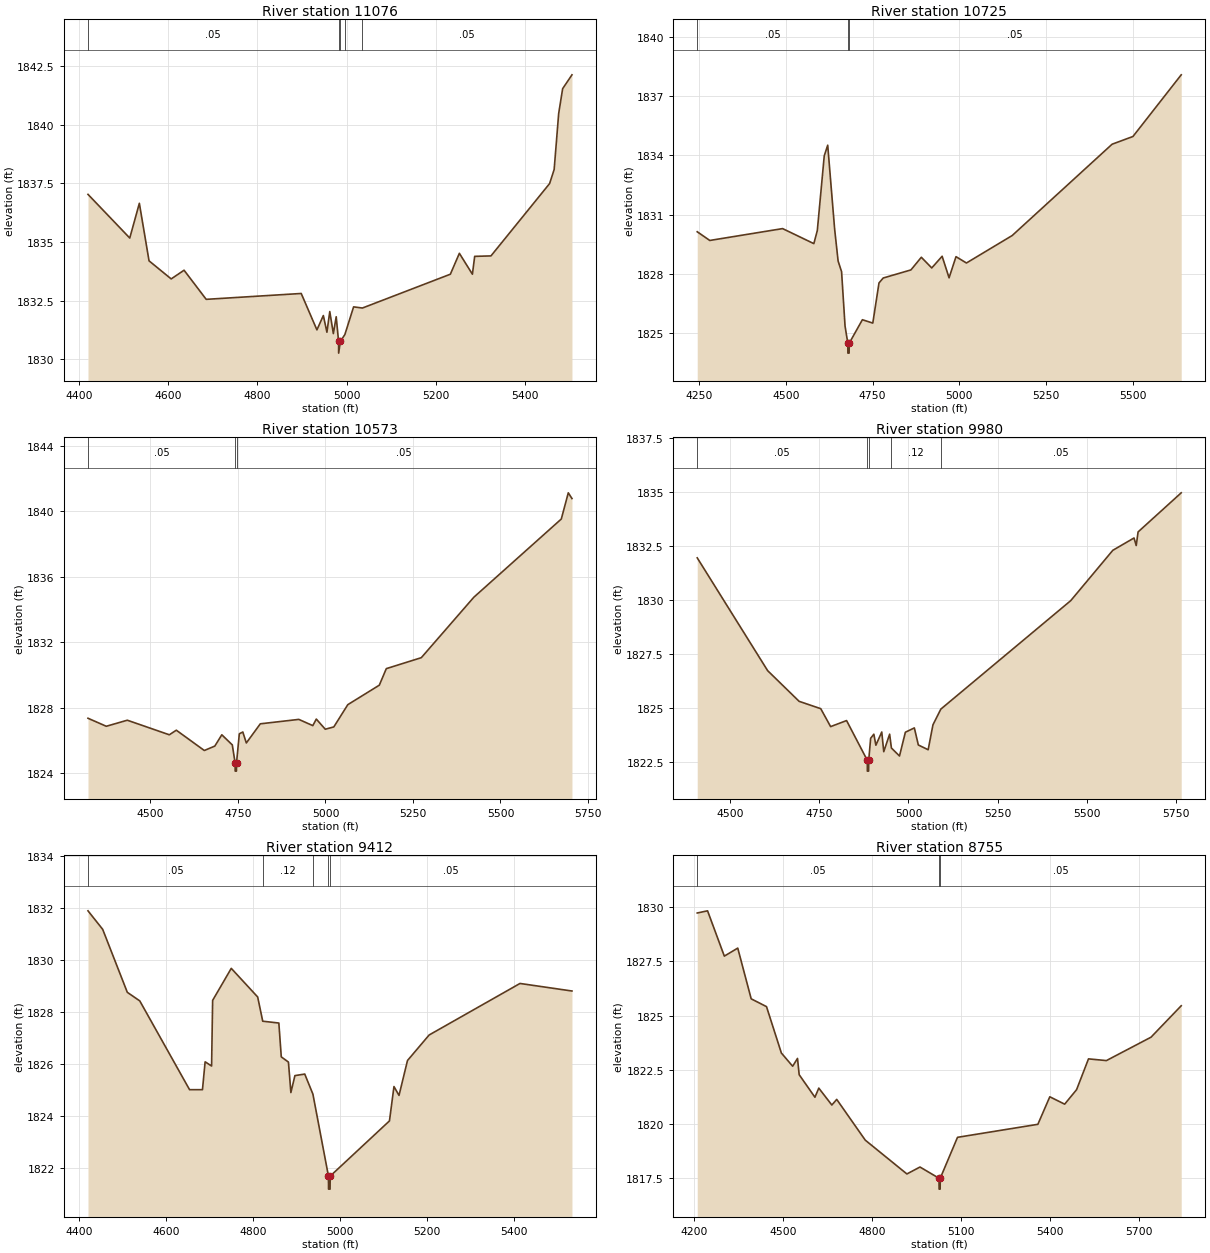
Type RM Length L Ch R = 1,11076,351,351,351
BEGIN DESCRIPTION:
Elm 01 96 10886.4
END DESCRIPTION:
XS GIS Cut Line= 3
      1605165.16      6805300.10      1605617.58      6804937.81
      1605692.52      6804438.50
#Sta/Elev= 30
  4420.4 1837.03  4514.0 1835.17  4535.5 1836.65  4557.2 1834.20  4606.8 1833.43
  4635.7 1833.80  4685.3 1832.56  4898.2 1832.81  4933.4 1831.26  4947.8 1831.87
  4955.8 1831.16  4962.2 1832.04  4970.2 1831.10  4976.6 1831.82  4981.9 1830.77
  4982.1 1830.27  4985.9 1830.77  4996.0 1831.06  5015.6 1832.24  5035.3 1832.19
  5232.4 1833.63  5252.6 1834.52  5281.8 1833.63  5286.9 1834.39  5323.4 1834.41
  5454.8 1837.49  5465.0 1838.09  5475.1 1840.47  5484.0 1841.53  5504.9 1842.12
#Mann=5,-1,0
  4420.4    0.05       0  4981.9    0.07       0  4985.9    0.05       0
  4996.0    0.12       0  5035.3    0.05       0
Bank Sta=4981.9,4985.9
Exp/Cntr=0.3,0.1

Type RM Length L Ch R = 1,10725,152,152,152
BEGIN DESCRIPTION:
Elm 01 96 10418.78
END DESCRIPTION:
XS GIS Cut Line= 3
      1605809.71      6805914.20      1605824.47      6805158.54
      1605805.37      6804518.83
#Sta/Elev= 30
  4244.2 1830.14  4280.4 1829.70  4490.4 1830.30  4580.5 1829.54  4590.5 1830.20
  4610.5 1833.98  4620.5 1834.52  4640.5 1830.27  4650.5 1828.66  4660.5 1828.12
  4670.5 1825.37  4678.5 1824.50  4678.7 1824.00  4682.2 1824.00  4682.5 1824.50
  4720.5 1825.69  4750.5 1825.52  4768.4 1827.55  4780.5 1827.80  4860.5 1828.21
  4890.5 1828.85  4920.5 1828.31  4950.5 1828.90  4970.5 1827.81  4990.5 1828.88
  5020.6 1828.56  5152.6 1829.95  5440.7 1834.57  5500.8 1834.96  5640.0 1838.08
#Mann=3,-1,0
  4244.2    0.05       0  4678.5    0.03       0  4682.5    0.05       0
Bank Sta=4678.5,4682.5
Exp/Cntr=0.3,0.1

Type RM Length L Ch R = 1,10573,593,593,593
BEGIN DESCRIPTION:
Elm 01 96 9961.169
END DESCRIPTION:
XS GIS Cut Line= 3
      1605949.03      6805910.35      1605953.14      6805231.76
      1605962.05      6804527.52
#Sta/Elev= 30
  4321.4 1827.35  4373.7 1826.86  4433.7 1827.23  4553.8 1826.34  4573.8 1826.62
  4653.8 1825.38  4683.8 1825.65  4703.8 1826.34  4733.8 1825.72  4741.8 1824.62
  4742.0 1824.12  4745.5 1824.12  4745.8 1824.62  4753.8 1826.40  4763.8 1826.51
  4773.8 1825.84  4813.8 1827.01  4923.8 1827.28  4963.8 1826.90  4973.8 1827.30
  4999.4 1826.68  5023.8 1826.82  5063.8 1828.18  5153.8 1829.37  5173.8 1830.38
  5273.8 1831.05  5423.8 1834.74  5673.8 1839.52  5693.8 1841.12  5704.3 1840.77
#Mann=3,-1,0
  4321.4    0.05       0  4741.8    0.03       0  4745.8    0.05       0
Bank Sta=4741.8,4745.8
Exp/Cntr=0.3,0.1

Type RM Length L Ch R = 1,9980,568,568,568
BEGIN DESCRIPTION:
Elm 01 96 9979.57
END DESCRIPTION:
XS GIS Cut Line= 3
      1605939.69      6806220.02      1606213.13      6805693.96
      1606436.58      6804961.26
#Sta/Elev= 30
  4406.9 1831.96  4604.6 1826.74  4693.0 1825.32  4753.7 1824.98  4781.4 1824.15
  4826.2 1824.43  4884.4 1822.59  4884.6 1822.09  4888.1 1822.09  4888.4 1822.59
  4893.8 1823.61  4902.8 1823.80  4908.5 1823.29  4925.0 1823.90  4930.6 1822.99
  4947.1 1823.80  4952.1 1823.16  4974.8 1822.79  4991.3 1823.89  5016.5 1824.09
  5027.7 1823.30  5055.3 1823.08  5068.7 1824.23  5090.9 1824.96  5455.6 1829.98
  5573.8 1832.31  5633.3 1832.88  5639.5 1832.53  5644.7 1833.16  5765.8 1834.97
#Mann=5,-1,0
  4406.9    0.05       0  4884.4    0.07       0  4888.4    0.05       0
  4952.1    0.12       0  5090.9    0.05       0
Bank Sta=4884.4,4888.4
Exp/Cntr=0.3,0.1

Type RM Length L Ch R = 1,9412,657,657,657
BEGIN DESCRIPTION:
Elm 01 96 9412.43
END DESCRIPTION:
XS GIS Cut Line= 5
      1605997.00      6806295.52      1606233.97      6806131.46
      1606374.59      6806108.02      1606504.80      6806040.32
      1606645.29      6805522.58
#Sta/Elev= 30
  4420.1 1831.89  4453.9 1831.18  4510.6 1828.76  4539.3 1828.43  4653.9 1825.02
  4683.6 1825.02  4689.7 1826.09  4704.6 1825.93  4707.0 1828.45  4749.9 1829.68
  4810.7 1828.58  4822.3 1827.65  4859.4 1827.58  4865.0 1826.28  4881.5 1826.08
  4887.1 1824.91  4896.4 1825.56  4919.0 1825.62  4937.8 1824.85  4973.6 1821.70
  4973.8 1821.20  4977.3 1821.20  4977.6 1821.70  5114.0 1823.82  5124.4 1825.14
  5136.0 1824.80  5155.5 1826.14  5205.3 1827.12  5414.5 1829.10  5534.1 1828.81
#Mann=5,-1,0
  4420.1    0.05       0  4822.3    0.12       0  4937.8    0.05       0
  4973.6    0.05       0  4977.6    0.05       0
Bank Sta=4973.6,4977.6
Exp/Cntr=0.3,0.1

Type RM Length L Ch R = 1,8755,592,592,592
BEGIN DESCRIPTION:
Elm 01 96 8755.32
END DESCRIPTION:
XS GIS Cut Line= 3
      1606274.25      6806672.35      1606974.77      6806302.56
      1607042.47      6805466.62
#Sta/Elev= 30
  4211.1 1829.73  4245.9 1829.83  4302.4 1827.74  4347.6 1828.11  4392.9 1825.77
  4444.5 1825.41  4494.6 1823.27  4532.6 1822.66  4549.0 1823.02  4554.6 1822.27
  4607.7 1821.23  4620.7 1821.65  4664.7 1820.87  4681.1 1821.13  4777.3 1819.25
  4917.6 1817.69  4961.7 1818.01  5025.9 1817.49  5026.1 1816.99  5029.6 1816.99
  5029.9 1817.49  5088.1 1819.38  5358.9 1819.98  5399.1 1821.25  5449.2 1820.91
  5489.4 1821.58  5529.5 1823.00  5589.7 1822.92  5740.2 1824.00  5841.9 1825.45
#Mann=3,-1,0
  4211.1    0.05       0  5025.9    0.05       0  5029.9    0.05       0
Bank Sta=5025.9,5029.9
Exp/Cntr=0.3,0.1

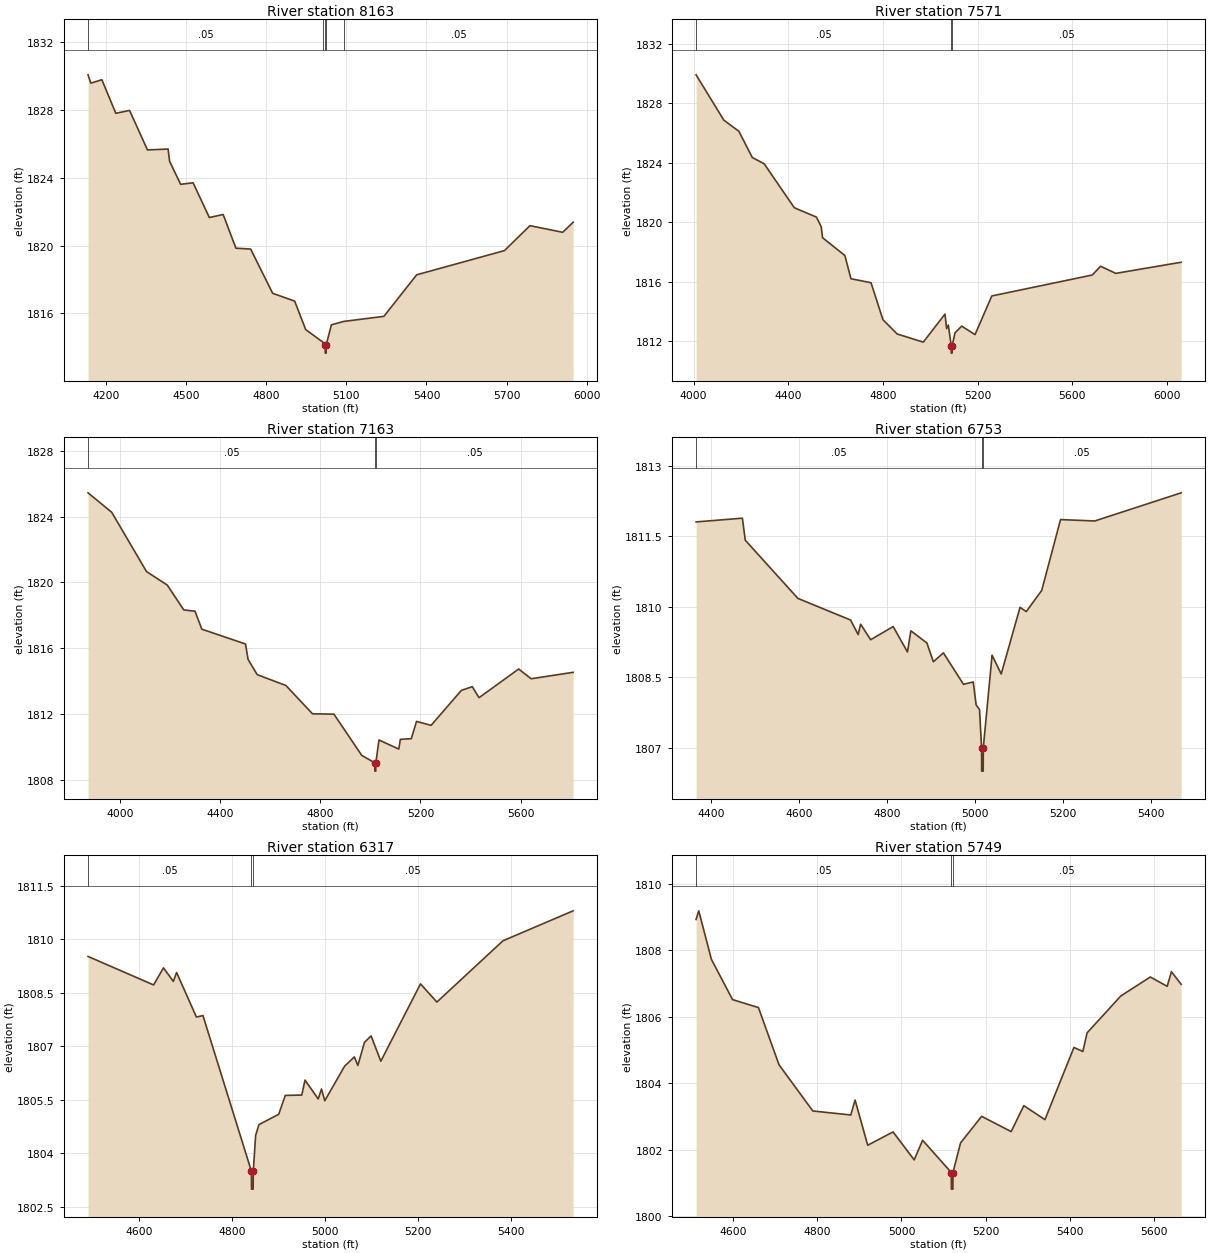
Type RM Length L Ch R = 1,8163,592,592,592
BEGIN DESCRIPTION:
Elm 01 96 8163.48
END DESCRIPTION:
XS GIS Cut Line= 3
      1606414.08      6806976.52      1607255.24      6806768.18
      1607742.23      6805953.05
#Sta/Elev= 30
  4132.9 1830.08  4143.3 1829.59  4184.7 1829.79  4236.9 1827.81  4288.4 1827.98
  4355.4 1825.65  4432.6 1825.70  4438.2 1824.98  4479.6 1823.62  4526.2 1823.71
  4587.1 1821.66  4638.7 1821.84  4686.6 1819.85  4741.7 1819.80  4824.1 1817.19
  4906.5 1816.73  4947.7 1815.05  5011.0 1814.32  5020.7 1814.16  5021.0 1813.66
  5024.5 1813.66  5024.7 1814.16  5044.1 1815.33  5090.1 1815.53  5240.6 1815.83
  5363.2 1818.28  5692.0 1819.71  5787.3 1821.18  5909.9 1820.79  5949.0 1821.38
#Mann=5,-1,0
  4132.9    0.05       0  5011.0    0.12       0  5020.7    0.05       0
  5024.7    0.12       0  5090.1    0.05       0
Bank Sta=5020.7,5024.7
Exp/Cntr=0.3,0.1

Type RM Length L Ch R = 1,7571,408,408,408
BEGIN DESCRIPTION:
Elm 01 96 7570.83
END DESCRIPTION:
XS GIS Cut Line= 3
      1606578.19      6807328.07      1607565.13      6807244.74
      1608286.50      6806468.69
#Sta/Elev= 30
  4010.2 1829.92  4127.4 1826.87  4191.0 1826.12  4247.9 1824.35  4298.0 1823.93
  4425.3 1820.97  4518.8 1820.34  4538.9 1819.70  4544.9 1818.95  4639.2 1817.75
  4664.6 1816.19  4749.6 1815.92  4799.8 1813.43  4860.0 1812.47  4970.4 1811.92
  5062.1 1813.81  5068.9 1812.83  5076.3 1813.07  5088.4 1811.68  5088.7 1811.18
  5092.2 1811.18  5092.4 1811.68  5104.6 1812.55  5132.7 1813.00  5189.1 1812.43
  5260.0 1815.03  5684.6 1816.44  5719.8 1817.03  5783.8 1816.55  6060.2 1817.30
#Mann=3,-1,0
  4010.2    0.05       0  5088.4    0.05       0  5092.4    0.05       0
Bank Sta=5088.4,5092.4
Exp/Cntr=0.3,0.1

Type RM Length L Ch R = 1,7163,410,410,410
BEGIN DESCRIPTION:
Elm 01 96 7162.71
END DESCRIPTION:
XS GIS Cut Line= 3
      1606671.43      6807725.22      1607788.66      6807571.57
      1608437.11      6807084.58
#Sta/Elev= 30
  3871.5 1825.44  3966.1 1824.26  4105.1 1820.66  4188.0 1819.84  4254.2 1818.33
  4299.1 1818.25  4326.2 1817.16  4500.9 1816.26  4511.0 1815.33  4547.4 1814.40
  4662.4 1813.74  4768.5 1812.02  4854.2 1812.00  4965.3 1809.50  5017.7 1809.04
  5018.0 1808.54  5021.5 1808.54  5021.7 1809.04  5034.3 1810.43  5113.5 1809.88
  5119.7 1810.47  5163.4 1810.51  5184.3 1811.56  5242.6 1811.32  5363.4 1813.44
  5407.1 1813.67  5434.2 1813.00  5592.5 1814.74  5642.5 1814.15  5810.2 1814.54
#Mann=3,-1,0
  3871.5    0.05       0  5017.7    0.05       0  5021.7    0.05       0
Bank Sta=5017.7,5021.7
Exp/Cntr=0.3,0.1

Type RM Length L Ch R = 1,6753,436,436,436
BEGIN DESCRIPTION:
Elm 01 96 6753.32
END DESCRIPTION:
XS GIS Cut Line= 3
      1607489.61      6808060.87      1608057.35      6807795.23
      1608369.88      6807435.82
#Sta/Elev= 30
  4366.0 1811.81  4471.3 1811.89  4477.9 1811.42  4597.6 1810.18  4717.3 1809.72
  4734.6 1809.41  4740.2 1809.63  4763.0 1809.30  4814.2 1809.58  4846.7 1809.04
  4854.4 1809.49  4890.9 1809.23  4905.6 1808.83  4928.4 1809.02  4974.1 1808.35
  4996.3 1808.40  5002.9 1807.91  5010.6 1807.81  5015.2 1807.00  5015.4 1806.50
  5018.9 1806.50  5019.2 1807.00  5039.1 1808.97  5059.9 1808.57  5102.7 1809.99
  5116.9 1809.90  5152.0 1810.35  5194.8 1811.86  5272.6 1811.83  5469.1 1812.43
#Mann=3,-1,0
  4366.0    0.05       0  5015.2    0.05       0  5019.2    0.05       0
Bank Sta=5015.2,5019.2
Exp/Cntr=0.3,0.1

Type RM Length L Ch R = 1,6317,568,568,568
BEGIN DESCRIPTION:
Elm 01 96 6317.25
END DESCRIPTION:
XS GIS Cut Line= 3
      1608040.71      6808392.77      1608401.79      6808031.69
      1608755.97      6807635.85
#Sta/Elev= 30
  4491.1 1809.52  4631.9 1808.72  4653.1 1809.20  4674.3 1808.82  4681.3 1809.07
  4723.8 1807.82  4737.9 1807.86  4842.0 1803.49  4842.2 1802.99  4845.7 1802.99
  4846.0 1803.49  4851.1 1804.50  4858.1 1804.80  4900.6 1805.09  4914.7 1805.62
  4950.1 1805.63  4957.1 1806.05  4985.4 1805.52  4992.5 1805.80  4999.5 1805.47
  5042.1 1806.44  5063.1 1806.70  5070.6 1806.46  5084.8 1807.11  5099.0 1807.29
  5119.9 1806.58  5205.1 1808.75  5240.3 1808.24  5382.3 1809.96  5532.9 1810.80
#Mann=3,-1,0
  4491.1    0.05       0  4842.0    0.05       0  4846.0    0.05       0
Bank Sta=4842,4846
Exp/Cntr=0.3,0.1

Type RM Length L Ch R = 1,5749,394,394,394
BEGIN DESCRIPTION:
Elm 01 96 5749.19
END DESCRIPTION:
XS GIS Cut Line= 3
      1608158.71      6808462.25      1608644.85      6808431.00
      1609308.09      6808418.15
#Sta/Elev= 30
  4512.9 1808.92  4519.2 1809.18  4549.3 1807.72  4599.4 1806.51  4660.8 1806.27
  4709.6 1804.55  4789.8 1803.16  4879.9 1803.04  4890.0 1803.49  4920.0 1802.13
  4980.1 1802.53  5030.2 1801.69  5050.2 1802.28  5118.2 1801.31  5118.5 1800.81
  5122.0 1800.81  5122.2 1801.31  5140.2 1802.20  5190.2 1803.00  5260.2 1802.54
  5290.2 1803.32  5340.3 1802.90  5409.1 1805.07  5430.3 1804.95  5440.3 1805.51
  5520.3 1806.62  5590.3 1807.19  5630.3 1806.91  5640.3 1807.35  5663.4 1806.97
#Mann=3,-1,0
  4512.9    0.05       0  5118.2    0.05       0  5122.2    0.05       0
Bank Sta=5118.2,5122.2
Exp/Cntr=0.3,0.1

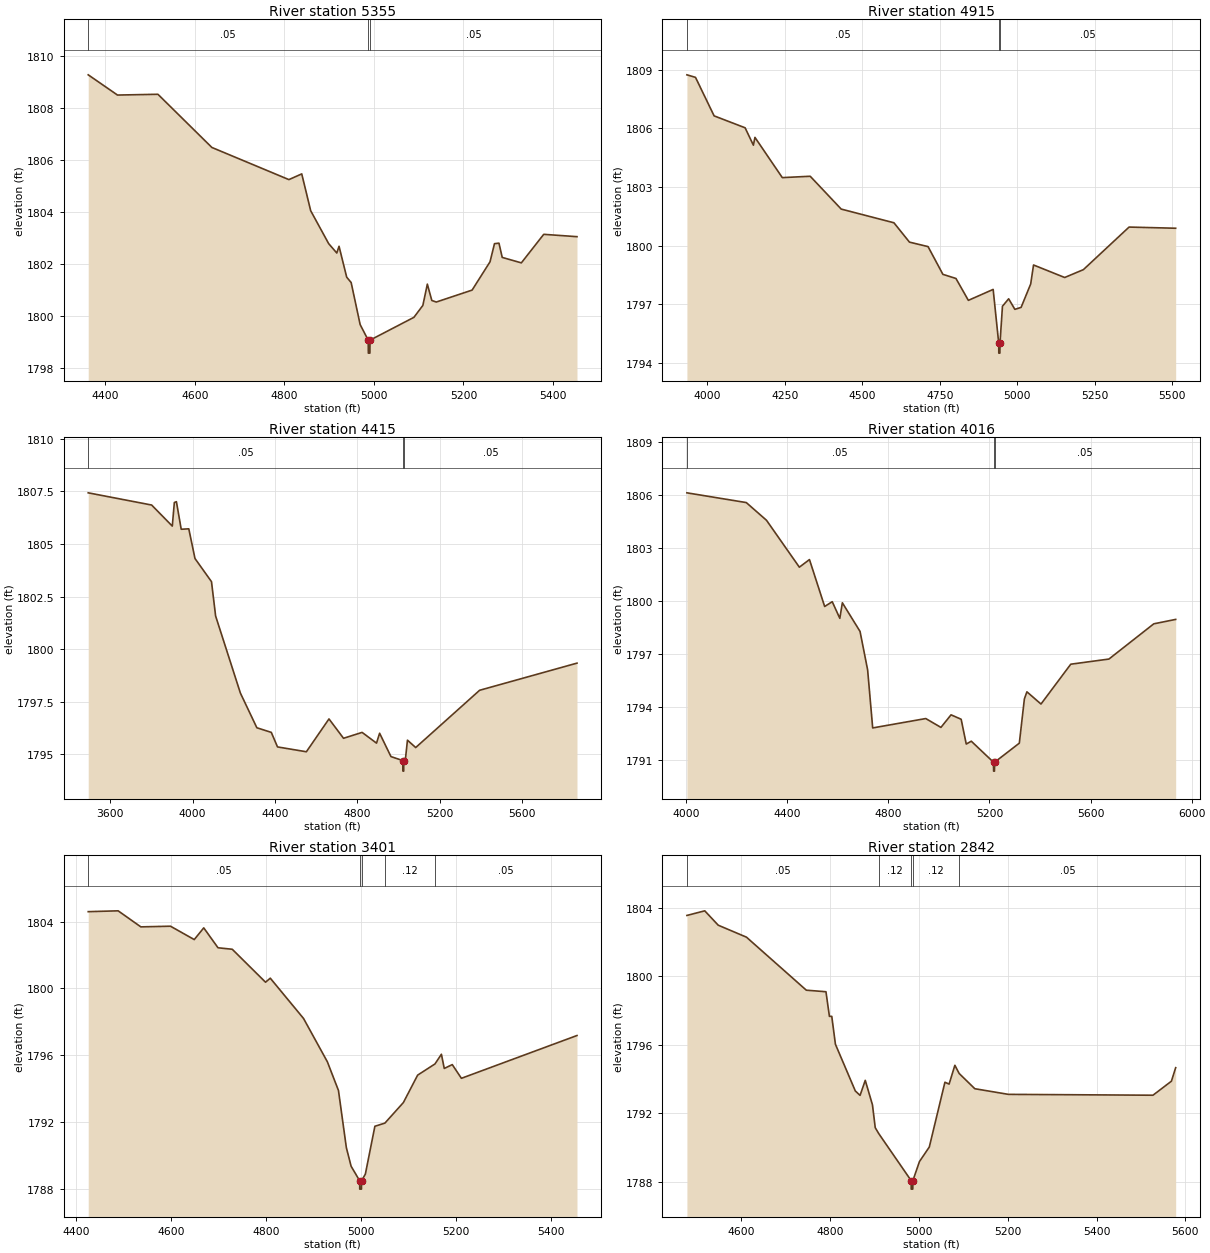
Type RM Length L Ch R = 1,5355,440,440,440
BEGIN DESCRIPTION:
Elm 01 96 5354.81
END DESCRIPTION:
XS GIS Cut Line= 3
      1608069.89      6808723.82      1608707.92      6808780.24
      1609159.28      6808784.58
#Sta/Elev= 30
  4361.7 1809.29  4427.1 1808.51  4517.4 1808.54  4637.9 1806.49  4810.0 1805.25
  4838.7 1805.47  4858.7 1804.05  4898.9 1802.78  4917.0 1802.42  4922.0 1802.68
  4939.1 1801.49  4949.1 1801.28  4969.2 1799.66  4987.2 1799.06  4987.5 1798.56
  4991.0 1798.56  4991.2 1799.06  5089.3 1799.94  5109.3 1800.40  5119.3 1801.22
  5129.3 1800.59  5139.3 1800.53  5219.3 1800.99  5259.3 1802.08  5269.3 1802.78
  5279.3 1802.80  5286.6 1802.25  5329.3 1802.04  5379.3 1803.14  5453.6 1803.05
#Mann=3,-1,0
  4361.7    0.05       0  4987.2    0.05       0  4991.2    0.05       0
Bank Sta=4987.2,4991.2
Exp/Cntr=0.3,0.1

Type RM Length L Ch R = 1,4915,500,500,500
BEGIN DESCRIPTION:
Elm 01 96 4914.9
END DESCRIPTION:
XS GIS Cut Line= 3
      1607527.34      6809166.53      1608590.74      6809149.17
      1609101.49      6809196.78
#Sta/Elev= 30
  3934.1 1808.74  3961.8 1808.61  4021.8 1806.64  4121.8 1806.03  4148.5 1805.14
  4153.5 1805.54  4241.8 1803.48  4331.8 1803.55  4431.8 1801.87  4601.8 1801.17
  4651.9 1800.18  4711.9 1799.95  4759.8 1798.53  4801.9 1798.32  4841.9 1797.20
  4921.9 1797.76  4939.9 1795.00  4940.1 1794.50  4943.6 1794.50  4943.9 1795.00
  4951.9 1796.90  4971.9 1797.28  4991.9 1796.74  5012.0 1796.84  5043.0 1798.04
  5052.1 1799.01  5152.6 1798.37  5212.8 1798.77  5360.3 1800.95  5510.6 1800.89
#Mann=3,-1,0
  3934.1    0.05       0  4939.9    0.05       0  4943.9    0.05       0
Bank Sta=4939.9,4943.9
Exp/Cntr=0.3,0.1

Type RM Length L Ch R = 1,4415,399,399,399
BEGIN DESCRIPTION:
Elm 01 96 4414.7
END DESCRIPTION:
XS GIS Cut Line= 3
      1606997.56      6809641.64      1608502.77      6809579.14
      1609367.35      6809573.93
#Sta/Elev= 30
  3493.7 1807.43  3801.4 1806.85  3901.5 1805.85  3911.5 1806.97  3921.5 1807.01
  3944.8 1805.70  3981.6 1805.72  4011.6 1804.31  4091.7 1803.21  4111.7 1801.58
  4231.8 1797.92  4311.8 1796.27  4381.9 1796.05  4411.9 1795.36  4552.0 1795.13
  4661.7 1796.69  4732.2 1795.77  4822.3 1796.05  4892.3 1795.54  4907.3 1796.01
  4962.4 1794.90  5020.4 1794.71  5020.7 1794.21  5024.2 1794.21  5024.4 1794.71
  5032.4 1794.77  5042.4 1795.68  5082.4 1795.33  5392.4 1798.05  5864.8 1799.34
#Mann=3,-1,0
  3493.7    0.05       0  5020.4    0.05       0  5024.4    0.05       0
Bank Sta=5020.4,5024.4
Exp/Cntr=0.3,0.1

Type RM Length L Ch R = 1,4016,615,615,615
BEGIN DESCRIPTION:
Mapping XS aec27d1a
END DESCRIPTION:
XS GIS Cut Line= 4
      1607300.23      6809858.78      1608167.45      6809843.15
      1608701.31      6809853.57      1609224.70      6809757.22
#Sta/Elev= 30
  4003.3 1806.11  4238.1 1805.56  4318.1 1804.56  4448.1 1801.91  4488.1 1802.34
  4548.2 1799.69  4578.2 1799.96  4608.2 1799.02  4618.2 1799.90  4688.2 1798.28
  4718.2 1796.11  4738.2 1792.83  4948.2 1793.36  5008.2 1792.86  5048.2 1793.57
  5088.2 1793.32  5108.3 1791.92  5128.3 1792.08  5216.3 1790.89  5216.5 1790.39
  5220.0 1790.39  5220.3 1790.89  5318.3 1791.97  5338.3 1794.47  5348.3 1794.87
  5404.0 1794.18  5521.8 1796.43  5672.7 1796.72  5850.2 1798.71  5936.8 1798.96
#Mann=3,-1,0
  4003.3    0.05       0  5216.3    0.03       0  5220.3    0.05       0
Bank Sta=5216.3,5220.3
Exp/Cntr=0.3,0.1

Type RM Length L Ch R = 1,3401,559,559,559
BEGIN DESCRIPTION:
Mapping XS 8a58018d
END DESCRIPTION:
XS GIS Cut Line= 3
      1607531.99      6810345.76      1608282.04      6810327.53
      1608541.25      6810226.43
#Sta/Elev= 30
  4426.3 1804.59  4489.3 1804.64  4537.0 1803.68  4599.4 1803.72  4649.4 1802.92
  4669.4 1803.62  4699.4 1802.43  4729.4 1802.34  4799.4 1800.37  4809.4 1800.61
  4879.4 1798.20  4929.5 1795.61  4952.9 1793.89  4969.5 1790.47  4979.5 1789.36
  4997.5 1788.49  4997.7 1787.99  5001.2 1787.99  5001.5 1788.49  5009.5 1788.89
  5029.5 1791.75  5050.6 1791.94  5089.5 1793.17  5119.5 1794.81  5156.0 1795.48
  5169.5 1796.06  5175.5 1795.21  5192.4 1795.44  5211.6 1794.62  5454.8 1797.18
#Mann=5,-1,0
  4426.3    0.05       0  4997.5    0.05       0  5001.5    0.05       0
  5050.6    0.12       0  5156.0    0.05       0
Bank Sta=4997.5,5001.5
Exp/Cntr=0.3,0.1

Type RM Length L Ch R = 1,2842,263,263,263
BEGIN DESCRIPTION:
Mapping XS 78d1a1a0
END DESCRIPTION:
XS GIS Cut Line= 4
      1607485.20      6810673.88      1607805.47      6810720.75
      1608196.10      6810918.67      1608534.62      6810900.44
#Sta/Elev= 30
  4477.6 1803.56  4517.8 1803.83  4548.1 1802.99  4611.7 1802.29  4746.5 1799.19
  4790.7 1799.10  4798.5 1797.66  4803.8 1797.66  4812.0 1796.03  4856.8 1793.30
  4867.5 1793.04  4879.2 1793.92  4895.4 1792.49  4901.7 1791.15  4910.0 1790.79
  4982.5 1788.06  4982.7 1787.56  4986.2 1787.56  4986.5 1788.06  5001.2 1789.17
  5023.4 1790.02  5058.6 1793.81  5068.0 1793.70  5081.0 1794.80  5090.7 1794.32
  5125.9 1793.43  5201.6 1793.10  5527.1 1793.05  5568.6 1793.87  5578.2 1794.66
#Mann=5,-1,0
  4477.6    0.05       0  4910.0    0.12       0  4982.5    0.07       0
  4986.5    0.12       0  5090.7    0.05       0
Bank Sta=4982.5,4986.5
Exp/Cntr=0.3,0.1

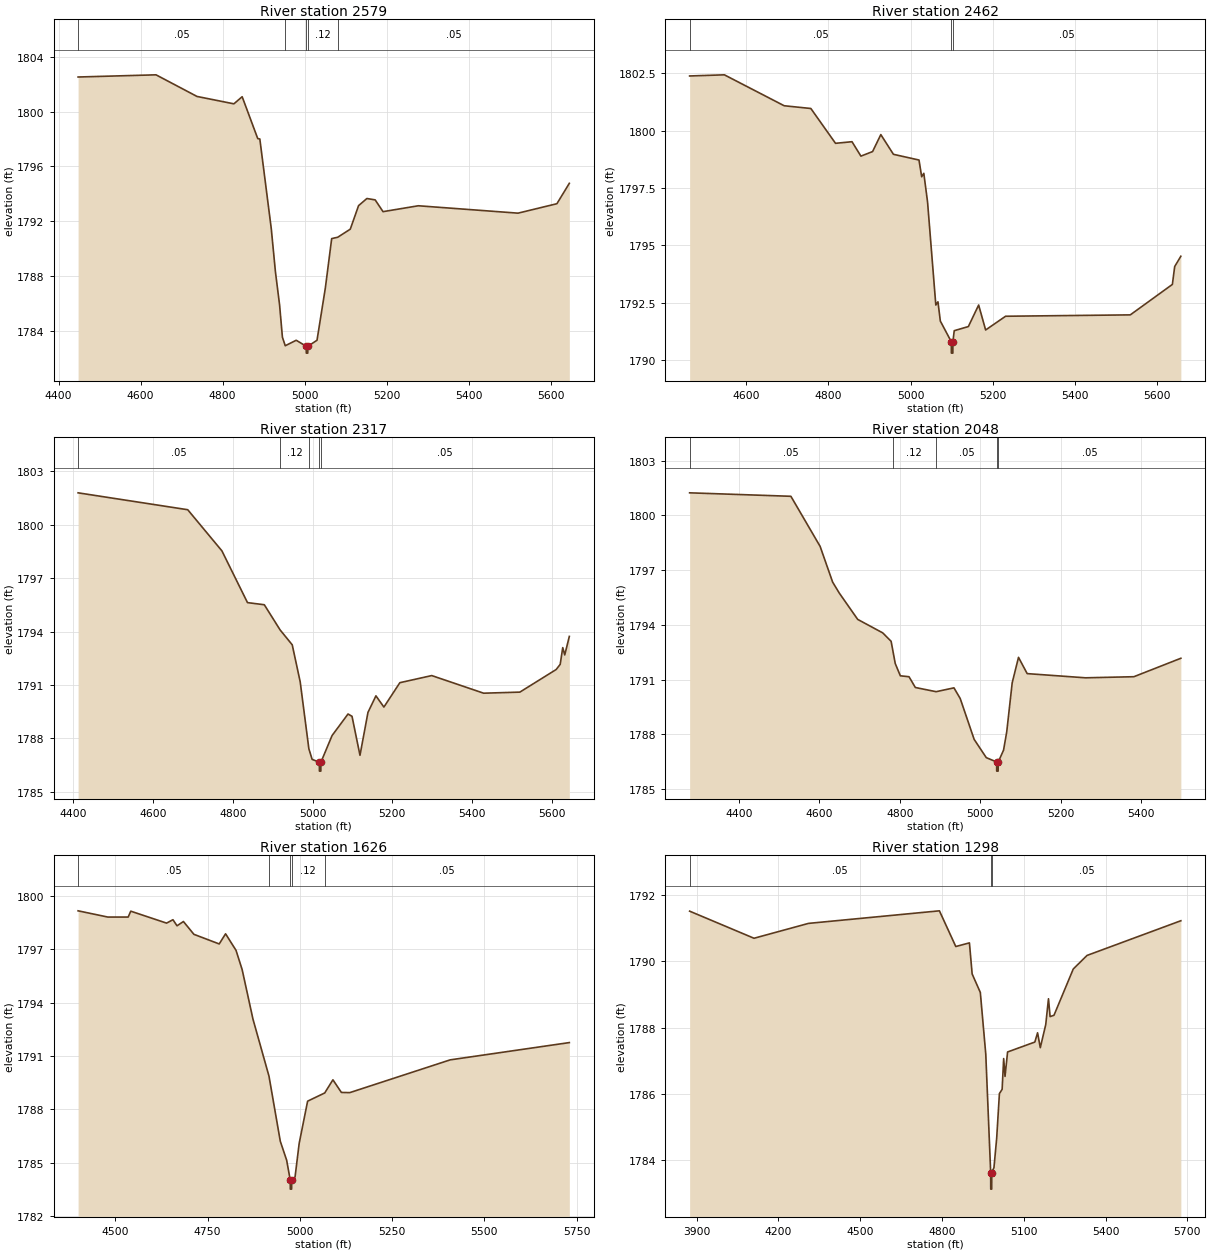
Type RM Length L Ch R = 1,2579,117,117,117
BEGIN DESCRIPTION:
Mapping XS e8006565
END DESCRIPTION:
XS GIS Cut Line= 4
      1607354.95      6811077.53      1607740.37      6811072.32
      1608060.68      6811017.63      1608545.09      6810957.73
#Sta/Elev= 30
  4447.4 1802.53  4637.5 1802.69  4737.5 1801.11  4827.5 1800.57  4847.7 1801.09
  4885.7 1798.03  4890.8 1798.00  4918.7 1791.45  4928.9 1788.28  4939.0 1785.87
  4945.9 1783.51  4952.8 1782.89  4979.6 1783.29  5004.0 1782.85  5004.2 1782.35
  5007.7 1782.35  5008.0 1782.85  5030.3 1783.29  5050.6 1787.10  5066.1 1790.72
  5080.9 1790.82  5111.5 1791.41  5131.7 1793.13  5152.0 1793.65  5172.2 1793.55
  5191.4 1792.69  5277.5 1793.12  5520.7 1792.58  5615.6 1793.27  5645.9 1794.76
#Mann=5,-1,0
  4447.4    0.05       0  4952.8    0.12       0  5004.0    0.07       0
  5008.0    0.12       0  5080.9    0.05       0
Bank Sta=5004,5008
Exp/Cntr=0.3,0.1

Type RM Length L Ch R = 1,2462,145,145,145
BEGIN DESCRIPTION:
Mapping XS 9915ceeb
END DESCRIPTION:
XS GIS Cut Line= 4
      1607370.59      6811150.44      1607847.14      6811176.48
      1608055.47      6811119.19      1608545.07      6811009.81
#Sta/Elev= 30
  4462.2 1802.39  4546.7 1802.44  4692.2 1801.09  4757.1 1800.97  4817.1 1799.45
  4857.2 1799.52  4878.9 1798.89  4907.3 1799.09  4927.3 1799.83  4958.0 1798.97
  5020.2 1798.72  5026.7 1797.99  5031.9 1798.14  5041.0 1796.89  5061.1 1792.39
  5066.3 1792.53  5072.1 1791.69  5098.7 1790.79  5099.0 1790.29  5102.5 1790.29
  5102.7 1790.79  5105.9 1791.27  5140.3 1791.45  5165.3 1792.39  5182.3 1791.30
  5230.8 1791.90  5534.2 1791.96  5636.6 1793.29  5642.2 1794.07  5657.2 1794.52
#Mann=3,-1,0
  4462.2    0.05       0  5098.7    0.05       0  5102.7    0.05       0
Bank Sta=5098.7,5102.7
Exp/Cntr=0.3,0.1

Type RM Length L Ch R = 1,2317,269,269,269
BEGIN DESCRIPTION:
Mapping XS bc039a23
END DESCRIPTION:
XS GIS Cut Line= 4
      1607323.72      6811233.78      1607745.58      6811304.09
      1608347.14      6811311.90      1608547.63      6811280.66
#Sta/Elev= 30
  4411.9 1801.80  4686.9 1800.85  4772.6 1798.54  4836.8 1795.63  4879.0 1795.51
  4918.8 1794.09  4949.0 1793.26  4969.0 1791.18  4990.8 1787.41  4999.0 1786.82
  5017.0 1786.66  5017.3 1786.16  5020.8 1786.16  5021.0 1786.66  5049.0 1788.16
  5089.0 1789.37  5099.0 1789.24  5119.0 1787.05  5139.0 1789.46  5159.0 1790.39
  5179.0 1789.76  5219.0 1791.13  5299.0 1791.53  5429.1 1790.54  5520.0 1790.60
  5611.1 1791.87  5621.2 1792.16  5627.6 1793.10  5632.6 1792.69  5644.1 1793.73
#Mann=5,-1,0
  4411.9    0.05       0  4918.8    0.12       0  4990.8    0.05       0
  5017.0    0.05       0  5021.0    0.05       0
Bank Sta=5017,5021
Exp/Cntr=0.3,0.1

Type RM Length L Ch R = 1,2048,422,422,422
BEGIN DESCRIPTION:
Mapping XS 6c4800e6
END DESCRIPTION:
XS GIS Cut Line= 4
      1607292.47      6811283.26      1607789.85      6811421.28
      1608188.29      6811653.05      1608431.49      6811671.16
#Sta/Elev= 30
  4277.3 1801.23  4529.0 1801.04  4601.6 1798.30  4632.8 1796.34  4649.3 1795.74
  4695.0 1794.30  4757.3 1793.56  4778.1 1793.10  4781.6 1792.69  4788.4 1791.88
  4801.1 1791.21  4822.6 1791.16  4838.3 1790.57  4890.0 1790.34  4934.3 1790.55
  4949.8 1789.97  4984.5 1787.73  5014.6 1786.73  5040.4 1786.49  5040.6 1785.99
  5044.1 1785.99  5044.4 1786.49  5057.6 1787.14  5065.5 1788.14  5079.1 1790.83
  5094.8 1792.22  5116.3 1791.33  5261.2 1791.10  5381.5 1791.16  5498.3 1792.17
#Mann=5,-1,0
  4277.3    0.05       0  4781.6    0.12       0  4890.0    0.05       0
  5040.4    0.05       0  5044.4    0.05       0
Bank Sta=5040.4,5044.4
Exp/Cntr=0.3,0.1

Type RM Length L Ch R = 1,1626,328,328,328
BEGIN DESCRIPTION:
Mapping XS 3a2dd457
END DESCRIPTION:
XS GIS Cut Line= 4
      1607091.97      6811502.02      1607823.70      6811843.15
      1608274.22      6811837.94      1608336.73      6811798.88
#Sta/Elev= 30
  4398.8 1799.15  4479.4 1798.80  4534.5 1798.80  4541.6 1799.13  4638.6 1798.46
  4655.9 1798.65  4667.0 1798.31  4684.3 1798.55  4712.7 1797.83  4781.3 1797.29
  4798.6 1797.86  4826.9 1796.93  4843.5 1795.85  4872.8 1793.07  4916.3 1789.86
  4946.9 1786.21  4964.2 1785.14  4973.9 1784.02  4974.1 1783.52  4977.6 1783.52
  4977.9 1784.02  4986.9 1784.20  4998.1 1786.09  5021.0 1788.46  5067.3 1788.92
  5089.6 1789.66  5112.5 1788.95  5135.3 1788.94  5407.5 1790.78  5730.4 1791.75
#Mann=5,-1,0
  4398.8    0.05       0  4916.3    0.12       0  4973.9    0.07       0
  4977.9    0.12       0  5067.3    0.05       0
Bank Sta=4973.9,4977.9
Exp/Cntr=0.3,0.1

Type RM Length L Ch R = 1,1298,0,0,0
BEGIN DESCRIPTION:
Elm 01 96 5193.894
END DESCRIPTION:
XS GIS Cut Line= 3
      1606428.88      6812028.05      1607751.80      6812056.69
      1608225.76      6811988.98
#Sta/Elev= 30
  3874.1 1791.52  4110.3 1790.70  4310.3 1791.15  4790.4 1791.53  4850.5 1790.45
  4900.5 1790.56  4910.5 1789.62  4940.5 1789.06  4960.5 1787.19  4978.5 1783.61
  4978.7 1783.11  4982.2 1783.11  4982.5 1783.61  4990.5 1783.76  5000.5 1784.65
  5010.5 1786.00  5020.5 1786.13  5026.1 1787.06  5031.1 1786.52  5040.5 1787.26
  5140.5 1787.56  5150.5 1787.84  5160.5 1787.39  5180.5 1788.09  5190.5 1788.87
  5196.4 1788.33  5210.7 1788.37  5281.4 1789.77  5331.9 1790.18  5676.1 1791.23
#Mann=3,-1,0
  3874.1    0.05       0  4978.5    0.05       0  4982.5    0.05       0
Bank Sta=4978.5,4982.5
Exp/Cntr=0.3,0.1

Chan Stop Cuts=-1