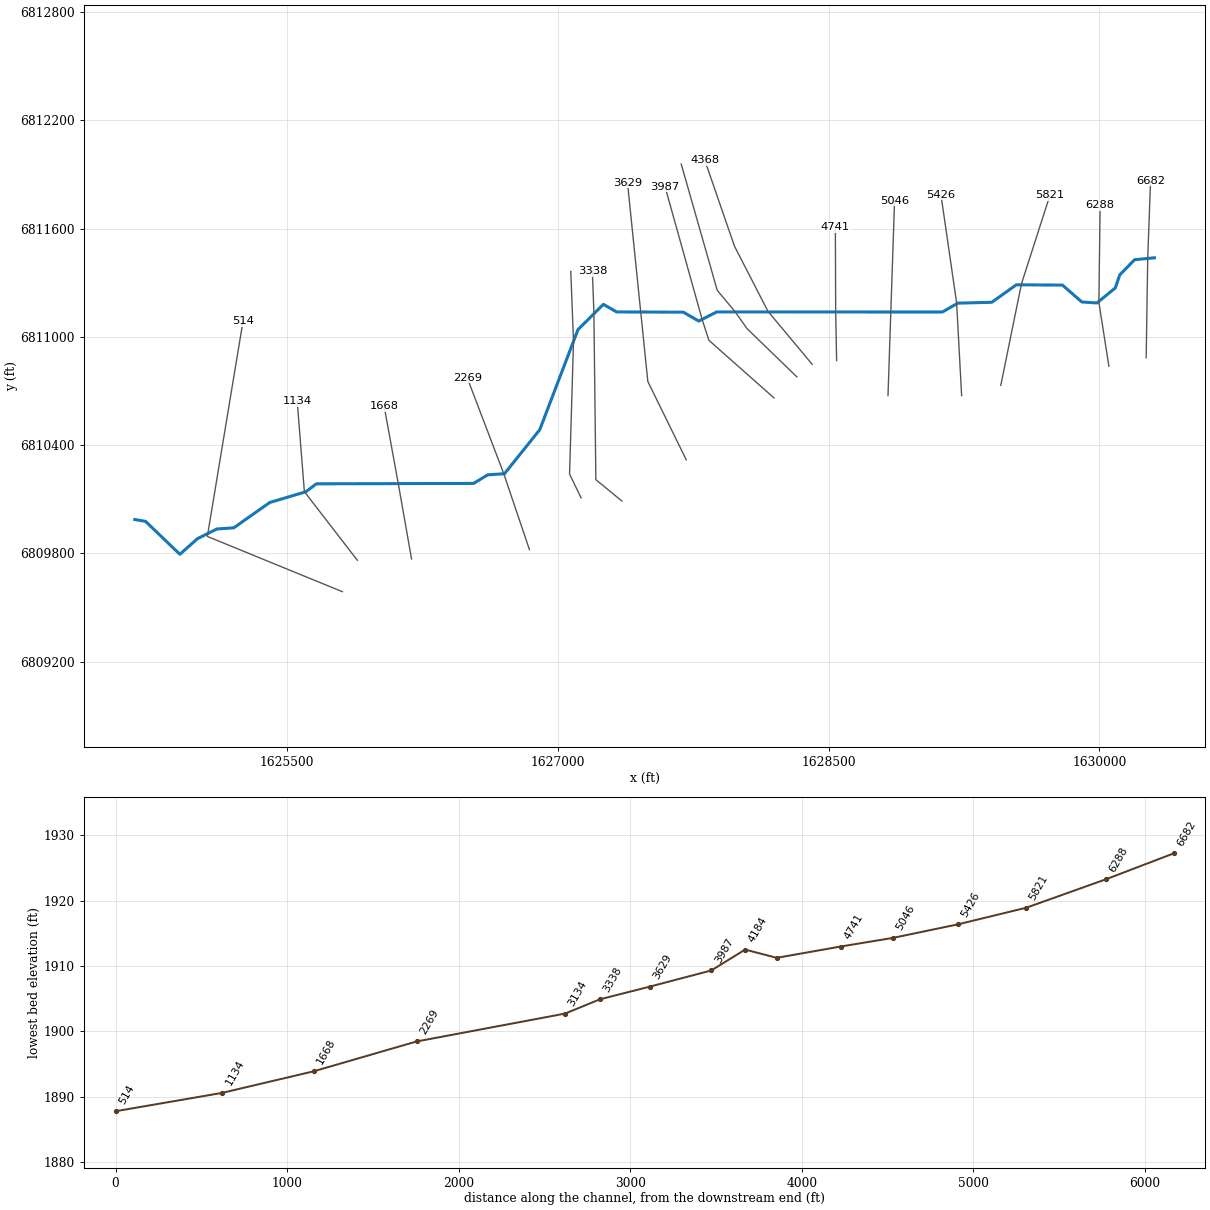
--- Elm 01 97.prj (project) ---

Proj Title=Elm 01 97 Base Level Engineering
Current Plan=p01
Default Exp/Contr=0.3,0.1
English Units
Geom File=g01
Flow File=f01
Plan File=p01
BEGIN DESCRIPTION:
Elm 01 97
END DESCRIPTION:

--- Elm 01 97.p01 (plan) ---

Plan Title=Multiple Run
Short Identifier=Multiple
Geom File=g01
Flow File=f01
Subcritical Flow
K Sum by GR= 0
Std Step Tol= 0.01
Critical Tol= 0.01
Num of Std Step Trials= 20
Max Error Tol= 0.3
Flow Tol Ratio= 0.001
Split Flow NTrial= 30
Split Flow Tol= 0.02
Split Flow Ratio= 0.02
Log Output Level= 0
Friction Slope Method= 1
Unsteady Friction Slope Method= 2
Unsteady Bridges Friction Slope Method= 1
Parabolic Critical Depth
Global Vel Dist=  1 , 1 , 1
Global Log Level= 0
CheckData=True
Encroach Param= -1, 0, 0, 0
BEGIN DESCRIPTION:
Multiple Run
END DESCRIPTION:

--- Elm 01 97.f01 (steady flow) ---

Flow Title=Multiple
Number of Profiles=7
Profile Names=10-year,25-year,50-year,1pct_min,100-year,1pct_plu,500-year
River Rch & RM= Elm 01 97,Reach-1,6682
     260     361     445     340     544     749     827
River Rch & RM= Elm 01 97,Reach-1,5821
     374     532     665     516     827    1140    1290
Boundary for River Rch & Prof#=Elm 01 97,Reach-1,1
Up Type=0
Dn Type=3
Dn Slope=0.001
Boundary for River Rch & Prof#=Elm 01 97,Reach-1,2
Up Type=0
Dn Type=3
Dn Slope=0.001
Boundary for River Rch & Prof#=Elm 01 97,Reach-1,3
Up Type=0
Dn Type=3
Dn Slope=0.001
Boundary for River Rch & Prof#=Elm 01 97,Reach-1,4
Up Type=0
Dn Type=3
Dn Slope=0.001
Boundary for River Rch & Prof#=Elm 01 97,Reach-1,5
Up Type=0
Dn Type=3
Dn Slope=0.001
Boundary for River Rch & Prof#=Elm 01 97,Reach-1,6
Up Type=0
Dn Type=3
Dn Slope=0.001
Boundary for River Rch & Prof#=Elm 01 97,Reach-1,7
Up Type=0
Dn Type=3
Dn Slope=0.001

--- Elm 01 97.g01 (geometry) ---

Geom Title=Existing Conditions

River Reach=Elm 01 97,Reach-1
Reach XY= 30
      1630305.00      6811438.00      1630195.16      6811427.58
      1630113.15      6811344.07      1630088.36      6811271.29
      1629986.72      6811187.92      1629902.58      6811193.41
      1629795.41      6811286.79      1629539.80      6811288.49
      1629403.53      6811191.55      1629215.51      6811186.78
      1629130.08      6811137.80      1627879.91      6811138.19
      1627780.00      6811087.60      1627694.50      6811136.76
      1627324.98      6811138.19      1627251.58      6811180.21
      1627110.83      6811040.30      1626899.16      6810485.71
      1626703.52      6810241.61      1626610.57      6810235.53
      1626532.31      6810187.90      1625660.94      6810185.74
      1625603.40      6810141.86      1625402.71      6810082.16
      1625203.42      6809941.83      1625110.56      6809935.56
      1625002.70      6809882.14      1624905.00      6809795.08
      1624714.79      6809977.48      1624655.00      6809988.00

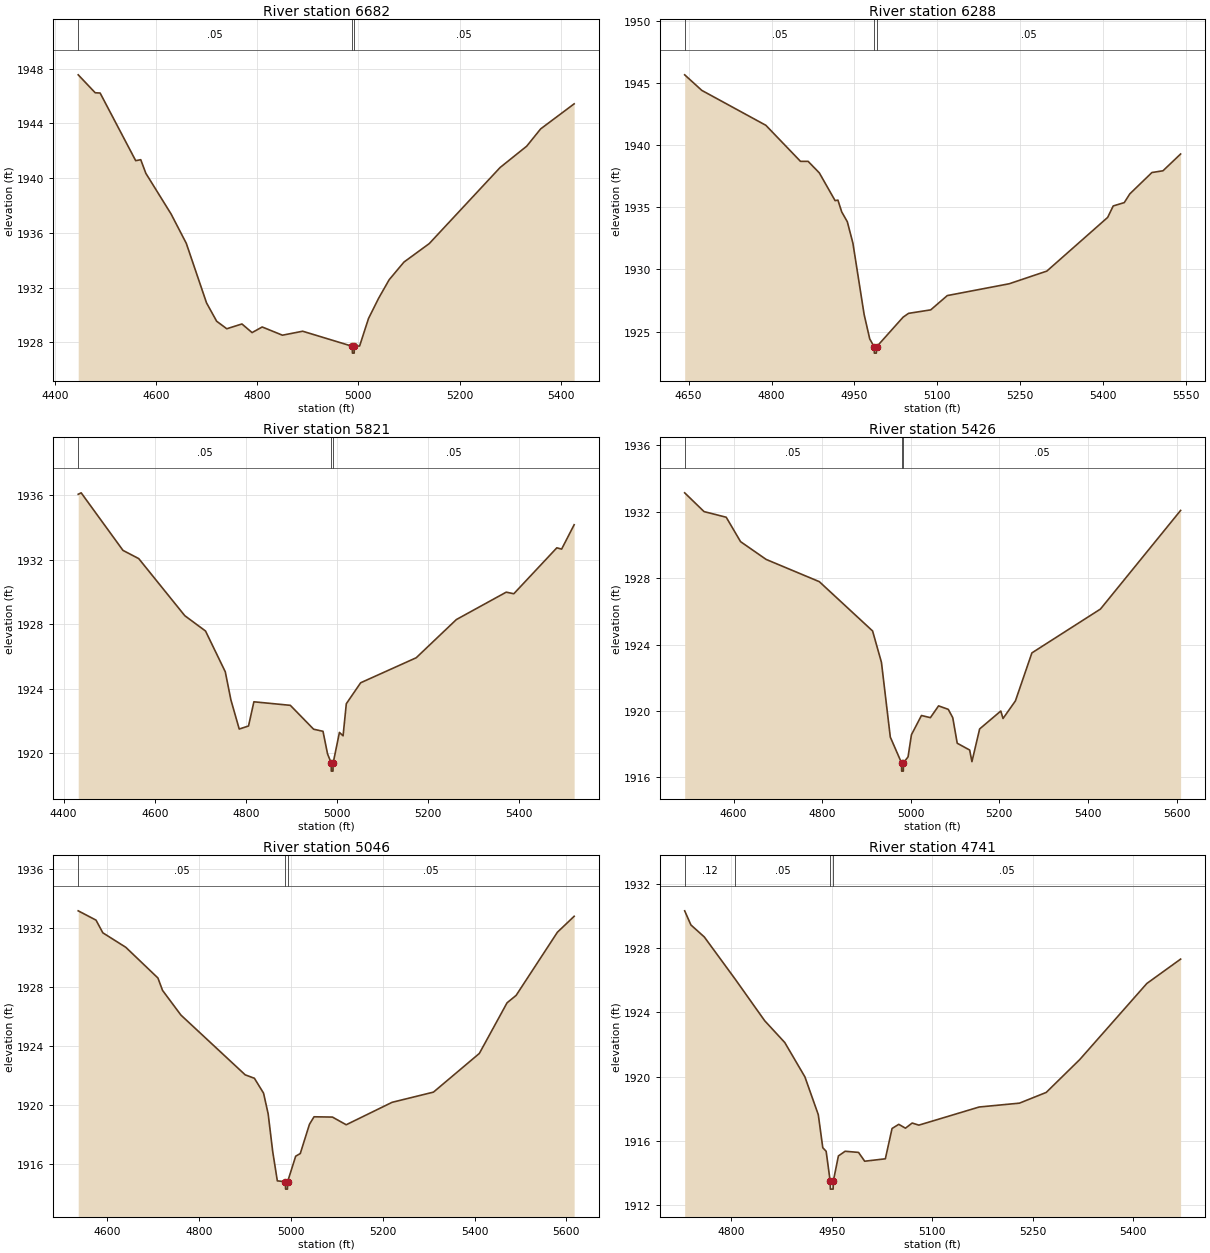
Type RM Length L Ch R = 1,6682,394,394,394
BEGIN DESCRIPTION:
Elm 01 97 6548.224
END DESCRIPTION:
XS GIS Cut Line= 3
      1630259.25      6810884.42      1630267.93      6811437.95
      1630283.51      6811864.17
#Sta/Elev= 30
  4446.4 1947.55  4480.0 1946.24  4489.7 1946.22  4560.0 1941.28  4570.0 1941.35
  4580.0 1940.36  4630.0 1937.38  4660.0 1935.24  4700.0 1930.89  4720.0 1929.55
  4740.0 1929.00  4770.0 1929.35  4790.0 1928.72  4810.0 1929.13  4850.0 1928.53
  4890.0 1928.82  4988.0 1927.72  4988.3 1927.22  4991.8 1927.22  4992.0 1927.72
  5002.5 1927.74  5020.1 1929.75  5040.1 1931.23  5060.9 1932.58  5090.1 1933.87
  5140.1 1935.22  5280.2 1940.78  5332.8 1942.34  5360.3 1943.60  5426.5 1945.43
#Mann=3,-1,0
  4446.4    0.05       0  4988.0    0.03       0  4992.0    0.05       0
Bank Sta=4988,4992
Exp/Cntr=0.3,0.1

Type RM Length L Ch R = 1,6288,467,467,467
BEGIN DESCRIPTION:
Elm 01 97 6288.18
END DESCRIPTION:
XS GIS Cut Line= 3
      1630052.66      6810837.47      1629997.09      6811191.67
      1630004.04      6811729.89
#Sta/Elev= 30
  4643.0 1945.66  4673.9 1944.41  4789.8 1941.60  4852.4 1938.70  4866.2 1938.70
  4886.5 1937.77  4915.0 1935.54  4920.1 1935.58  4927.0 1934.63  4937.1 1933.84
  4947.2 1932.12  4967.5 1926.38  4977.6 1924.42  4985.7 1923.77  4986.0 1923.27
  4989.6 1923.27  4989.9 1923.77  5037.9 1926.16  5047.9 1926.47  5087.9 1926.75
  5117.9 1927.90  5229.8 1928.85  5297.9 1929.87  5407.9 1934.19  5417.9 1935.11
  5437.9 1935.38  5447.9 1936.08  5487.9 1937.80  5507.9 1937.94  5539.8 1939.29
#Mann=3,-1,0
  4643.0    0.05       0  4985.7    0.05       0  4989.9    0.05       0
Bank Sta=4985.7,4989.9
Exp/Cntr=0.3,0.1

Type RM Length L Ch R = 1,5821,395,395,395
BEGIN DESCRIPTION:
Elm 01 97 5821.1
END DESCRIPTION:
XS GIS Cut Line= 3
      1629453.70      6810731.64      1629568.27      6811294.10
      1629725.86      6811784.18
#Sta/Elev= 30
  4431.9 1936.07  4438.4 1936.16  4530.2 1932.59  4564.8 1932.08  4665.9 1928.54
  4711.4 1927.59  4754.8 1925.06  4767.1 1923.32  4785.4 1921.51  4805.8 1921.70
  4817.6 1923.20  4897.6 1922.98  4948.7 1921.50  4969.3 1921.37  4979.3 1919.97
  4987.4 1919.40  4987.6 1918.90  4991.3 1918.90  4991.6 1919.40  5005.4 1921.30
  5013.4 1921.09  5020.5 1923.08  5052.0 1924.38  5173.9 1925.93  5262.1 1928.30
  5371.6 1930.00  5388.2 1929.90  5482.7 1932.75  5493.2 1932.67  5520.7 1934.18
#Mann=3,-1,0
  4431.9    0.05       0  4987.4    0.05       0  4991.6    0.05       0
Bank Sta=4987.4,4991.6
Exp/Cntr=0.3,0.1

Type RM Length L Ch R = 1,5426,380,380,380
BEGIN DESCRIPTION:
Elm 01 97 5425.86
END DESCRIPTION:
XS GIS Cut Line= 3
      1629236.67      6810674.36      1629208.90      6811188.20
      1629122.10      6811787.15
#Sta/Elev= 30
  4489.5 1933.14  4533.2 1932.01  4583.3 1931.67  4615.7 1930.20  4673.4 1929.13
  4793.5 1927.79  4913.8 1924.82  4933.8 1922.93  4953.8 1918.43  4979.1 1916.88
  4979.4 1916.38  4983.2 1916.38  4983.5 1916.88  4993.9 1917.24  5001.5 1918.57
  5024.1 1919.73  5044.3 1919.60  5062.8 1920.31  5084.7 1920.10  5094.8 1919.60
  5104.9 1918.06  5133.0 1917.65  5138.1 1916.95  5155.5 1918.92  5203.3 1920.00
  5208.3 1919.55  5236.3 1920.61  5273.5 1923.50  5428.3 1926.14  5609.3 1932.08
#Mann=3,-1,0
  4489.5    0.05       0  4979.1    0.05       0  4983.5    0.05       0
Bank Sta=4979.1,4983.5
Exp/Cntr=0.3,0.1

Type RM Length L Ch R = 1,5046,305,305,305
BEGIN DESCRIPTION:
Elm 01 97 5046.02
END DESCRIPTION:
XS GIS Cut Line= 3
      1628828.69      6810674.35      1628844.32      6811139.59
      1628865.10      6811754.44
#Sta/Elev= 30
  4536.2 1933.15  4575.0 1932.52  4589.9 1931.66  4639.9 1930.68  4709.9 1928.60
  4720.0 1927.76  4760.0 1926.09  4900.1 1922.04  4920.1 1921.81  4940.1 1920.80
  4950.1 1919.40  4960.1 1916.83  4970.1 1914.86  4987.8 1914.80  4988.1 1914.30
  4992.1 1914.30  4992.5 1914.80  5010.1 1916.53  5020.1 1916.71  5040.1 1918.69
  5050.1 1919.20  5090.2 1919.18  5120.2 1918.66  5220.2 1920.18  5310.3 1920.87
  5410.3 1923.49  5470.7 1926.92  5490.4 1927.42  5580.4 1931.70  5616.9 1932.78
#Mann=3,-1,0
  4536.2    0.05       0  4987.8    0.03       0  4992.5    0.05       0
Bank Sta=4987.8,4992.5
Exp/Cntr=0.3,0.1

Type RM Length L Ch R = 1,4741,373,373,373
BEGIN DESCRIPTION:
Elm 01 97 4740.58
END DESCRIPTION:
XS GIS Cut Line= 3
      1628543.97      6810868.73      1628538.76      6811141.32
      1628537.02      6811608.38
#Sta/Elev= 30
  4730.7 1930.33  4740.0 1929.45  4760.0 1928.70  4806.4 1926.05  4850.0 1923.48
  4880.0 1922.12  4910.0 1919.98  4930.0 1917.62  4936.7 1915.56  4941.7 1915.34
  4947.7 1913.48  4948.0 1912.98  4952.1 1912.98  4952.4 1913.48  4960.0 1915.05
  4970.0 1915.34  4990.0 1915.27  4999.2 1914.72  5030.0 1914.87  5040.0 1916.76
  5050.0 1917.02  5060.0 1916.78  5070.0 1917.10  5080.0 1916.97  5170.0 1918.10
  5230.0 1918.34  5270.0 1919.01  5320.0 1921.06  5420.0 1925.80  5470.4 1927.32
#Mann=4,-1,0
  4730.7    0.12       0  4806.4    0.05       0  4947.7    0.05       0
  4952.4    0.05       0
Bank Sta=4947.7,4952.4
Exp/Cntr=0.3,0.1

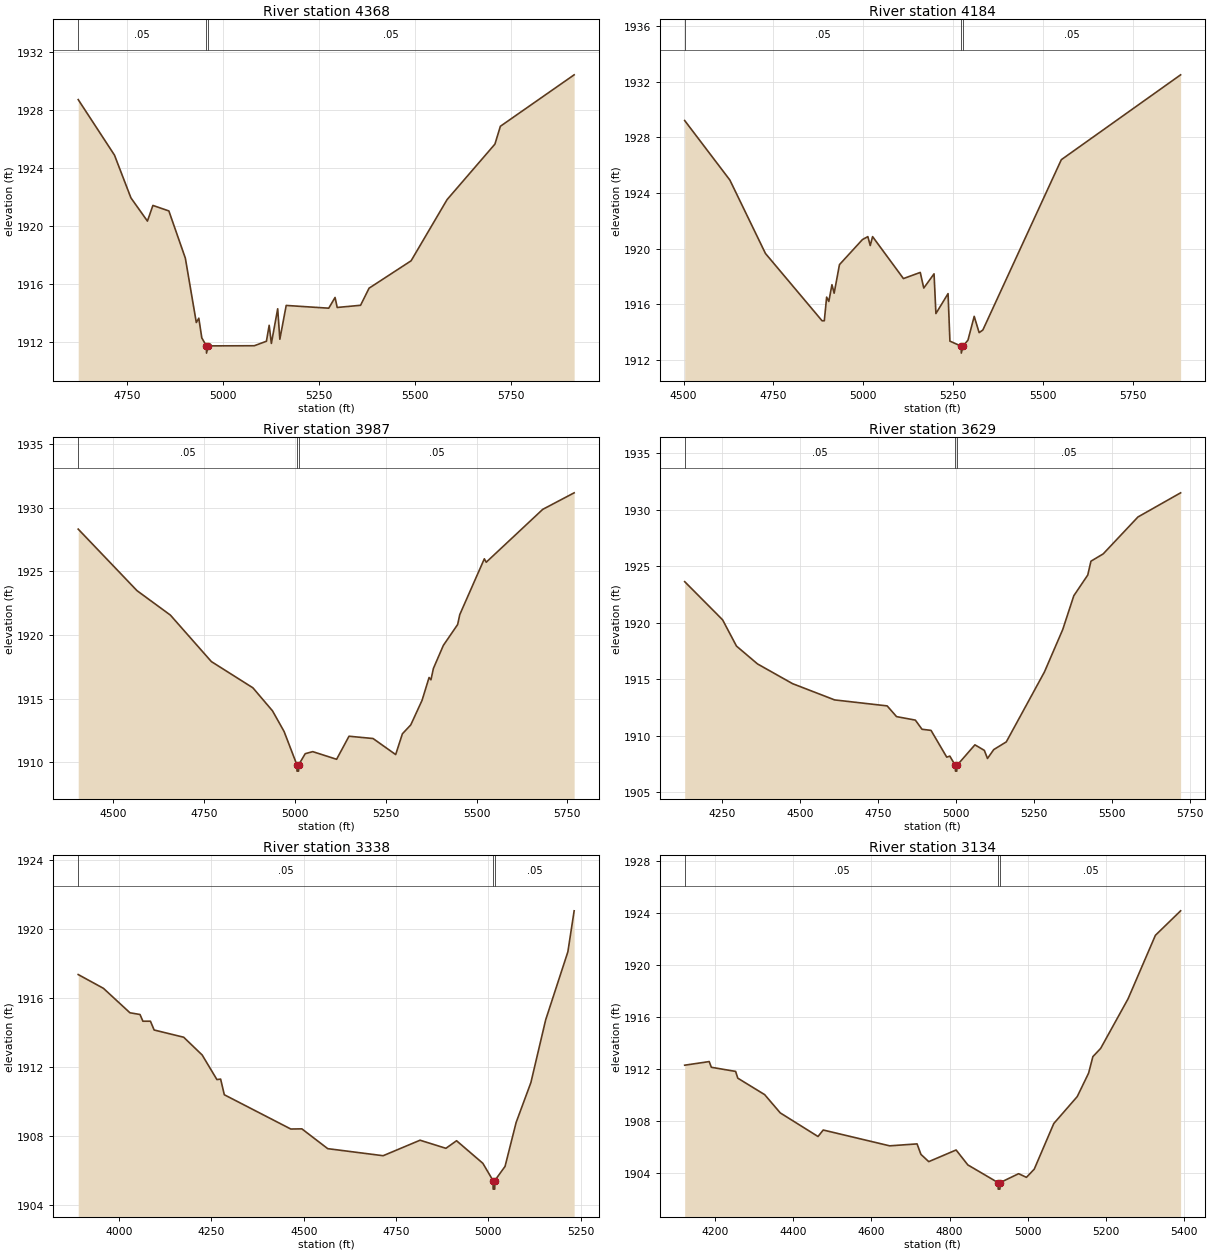
Type RM Length L Ch R = 1,4368,184,184,184
BEGIN DESCRIPTION:
Elm 01 97 4368.21
END DESCRIPTION:
XS GIS Cut Line= 4
      1628408.54      6810847.93      1628163.76      6811141.32
      1627978.00      6811502.44      1627813.07      6811979.86
#Sta/Elev= 30
  4622.1 1928.74  4716.7 1924.91  4759.6 1921.96  4802.6 1920.36  4816.9 1921.44
  4858.5 1921.06  4901.5 1917.80  4930.1 1913.36  4936.6 1913.66  4944.4 1912.30
  4956.4 1911.75  4956.7 1911.25  4961.2 1911.75  5081.4 1911.76  5112.9 1912.07
  5120.1 1913.17  5125.8 1911.92  5142.3 1914.31  5147.9 1912.21  5164.5 1914.54
  5275.4 1914.35  5291.9 1915.09  5297.5 1914.40  5358.4 1914.55  5380.6 1915.73
  5490.2 1917.62  5584.0 1921.84  5708.8 1925.67  5723.0 1926.90  5915.4 1930.45
#Mann=3,-1,0
  4622.1    0.05       0  4956.4    0.03       0  4961.2    0.05       0
Bank Sta=4956.4,4961.2
Exp/Cntr=0.3,0.1

Type RM Length L Ch R = 1,4184,197,197,197
BEGIN DESCRIPTION:
Elm 01 97 4184.23
END DESCRIPTION:
XS GIS Cut Line= 5
      1628323.50      6810778.46      1628047.44      6811045.84
      1627981.47      6811139.59      1627882.51      6811257.64
      1627682.85      6811957.32
#Sta/Elev= 30
  4502.8 1929.20  4628.6 1924.93  4727.7 1919.66  4885.3 1914.83  4891.5 1914.83
  4898.0 1916.53  4904.1 1916.22  4912.8 1917.42  4918.9 1916.81  4933.7 1918.86
  4997.7 1920.66  5012.7 1920.87  5019.4 1920.23  5025.9 1920.87  5111.8 1917.86
  5158.6 1918.30  5168.4 1917.18  5197.0 1918.20  5202.2 1915.35  5236.0 1916.78
  5241.2 1913.37  5272.5 1913.01  5272.9 1912.51  5277.5 1913.01  5291.4 1913.44
  5308.8 1915.15  5322.5 1913.98  5332.9 1914.17  5551.3 1926.39  5883.4 1932.48
#Mann=3,-1,0
  4502.8    0.05       0  5272.5    0.05       0  5277.5    0.05       0
Bank Sta=5272.5,5277.5
Exp/Cntr=0.3,0.1

Type RM Length L Ch R = 1,3987,358,358,358
BEGIN DESCRIPTION:
Elm 01 97 3986.86
END DESCRIPTION:
XS GIS Cut Line= 4
      1628196.74      6810661.73      1627836.50      6810980.73
      1627799.61      6811093.58      1627593.45      6811831.42
#Sta/Elev= 30
  4402.9 1928.32  4564.8 1923.49  4656.8 1921.57  4769.7 1917.92  4884.1 1915.86
  4938.1 1914.05  4970.0 1912.43  5005.2 1909.82  5005.6 1909.32  5009.8 1909.32
  5010.2 1909.82  5028.2 1910.69  5048.9 1910.85  5114.6 1910.25  5148.8 1912.06
  5215.0 1911.88  5277.3 1910.62  5295.8 1912.25  5318.9 1912.95  5350.0 1914.88
  5369.3 1916.67  5374.5 1916.49  5381.2 1917.38  5408.6 1919.19  5448.0 1920.83
  5453.9 1921.61  5521.5 1925.99  5526.7 1925.72  5682.3 1929.87  5768.9 1931.17
#Mann=3,-1,0
  4402.9    0.05       0  5005.2    0.05       0  5010.2    0.05       0
Bank Sta=5005.2,5010.2
Exp/Cntr=0.3,0.1

Type RM Length L Ch R = 1,3629,291,291,291
BEGIN DESCRIPTION:
Mapping XS 3d2cb4ce
END DESCRIPTION:
XS GIS Cut Line= 3
      1627710.55      6810318.88      1627497.89      6810752.87
      1627385.17      6811854.13
#Sta/Elev= 30
  4129.9 1923.64  4251.4 1920.26  4296.0 1917.93  4363.4 1916.35  4475.9 1914.60
  4610.8 1913.16  4779.2 1912.63  4809.3 1911.68  4869.6 1911.37  4890.9 1910.56
  4919.9 1910.46  4970.2 1908.09  4980.2 1908.18  4997.8 1907.35  4998.2 1906.85
  5002.4 1906.85  5002.8 1907.35  5060.6 1909.18  5090.8 1908.69  5100.9 1907.97
  5121.0 1908.76  5161.2 1909.44  5283.4 1915.63  5342.1 1919.39  5377.7 1922.39
  5422.5 1924.23  5432.6 1925.45  5472.0 1926.10  5583.4 1929.37  5720.2 1931.51
#Mann=3,-1,0
  4129.9    0.05       0  4997.8    0.05       0  5002.8    0.05       0
Bank Sta=4997.8,5002.8
Exp/Cntr=0.3,0.1

Type RM Length L Ch R = 1,3338,204,204,204
BEGIN DESCRIPTION:
Elm 01 97 3337.76
END DESCRIPTION:
XS GIS Cut Line= 4
      1627353.83      6810090.52      1627209.86      6810208.66
      1627198.99      6811136.86      1627190.38      6811365.00
#Sta/Elev= 30
  3889.5 1917.37  3957.8 1916.57  4029.6 1915.15  4056.8 1915.05  4064.7 1914.66
  4085.1 1914.66  4095.1 1914.15  4175.1 1913.73  4225.1 1912.70  4265.1 1911.27
  4275.1 1911.30  4285.1 1910.39  4465.1 1908.40  4495.1 1908.41  4565.1 1907.26
  4715.1 1906.85  4815.1 1907.75  4885.1 1907.28  4913.9 1907.72  4985.1 1906.41
  5012.6 1905.41  5013.0 1904.91  5017.3 1904.91  5017.6 1905.41  5045.2 1906.23
  5075.2 1908.78  5115.2 1911.10  5155.2 1914.74  5215.3 1918.69  5232.3 1921.07
#Mann=3,-1,0
  3889.5    0.05       0  5012.6    0.03       0  5017.6    0.05       0
Bank Sta=5012.6,5017.6
Exp/Cntr=0.3,0.1

Type RM Length L Ch R = 1,3134,865,865,865
BEGIN DESCRIPTION:
Elm 01 97 3134.44
END DESCRIPTION:
XS GIS Cut Line= 4
      1627128.08      6810107.95      1627064.11      6810239.79
      1627086.14      6810974.10      1627070.95      6811362.52
#Sta/Elev= 30
  4121.9 1912.28  4184.7 1912.56  4190.2 1912.12  4252.4 1911.80  4257.9 1911.28
  4326.7 1910.01  4366.7 1908.60  4463.3 1906.78  4476.7 1907.28  4646.8 1906.06
  4716.9 1906.21  4726.9 1905.40  4746.9 1904.84  4816.9 1905.74  4846.9 1904.59
  4924.4 1903.22  4924.8 1902.72  4929.1 1902.72  4929.4 1903.22  4977.0 1903.91
  4997.0 1903.63  5017.0 1904.26  5067.0 1907.78  5127.1 1909.86  5156.2 1911.67
  5167.1 1912.94  5187.1 1913.58  5257.2 1917.40  5327.2 1922.30  5391.8 1924.19
#Mann=3,-1,0
  4121.9    0.05       0  4924.4    0.03       0  4929.4    0.05       0
Bank Sta=4924.4,4929.4
Exp/Cntr=0.3,0.1

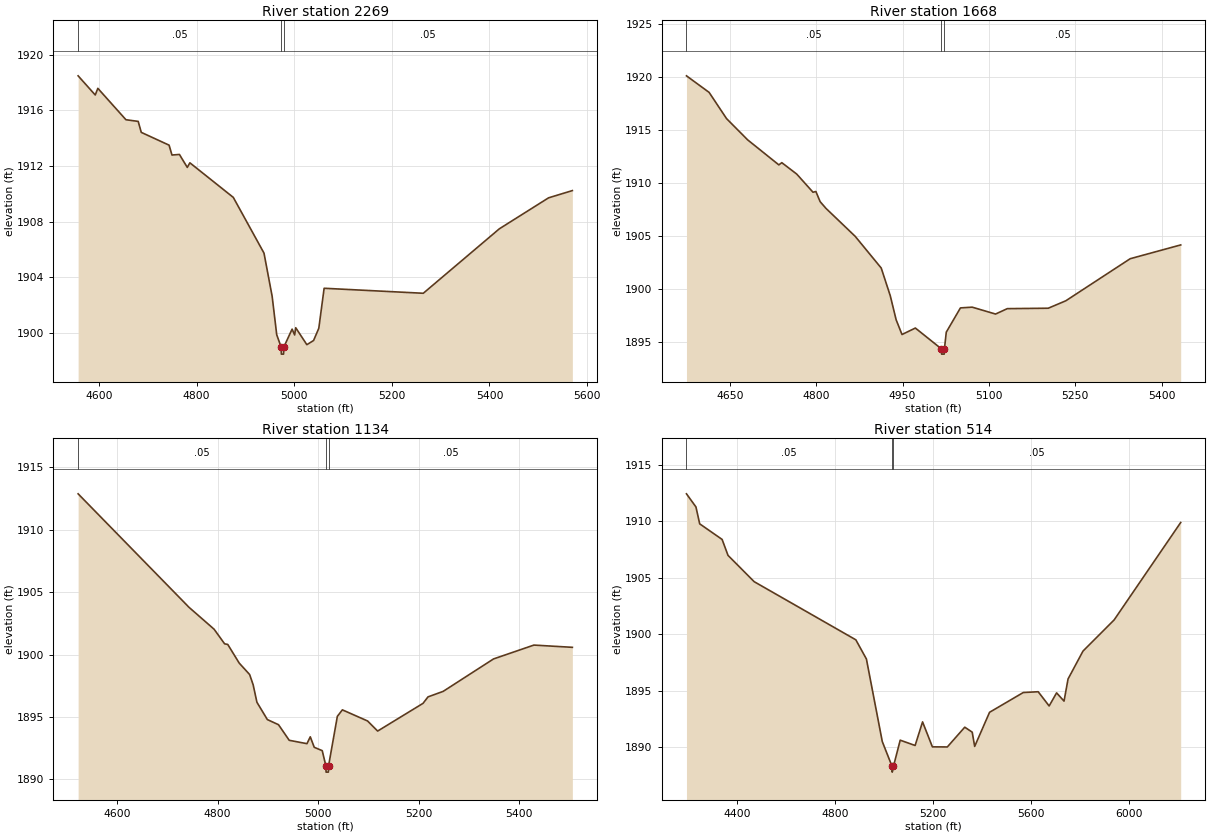
Type RM Length L Ch R = 1,2269,601,601,601
BEGIN DESCRIPTION:
Elm 01 97 2268.61
END DESCRIPTION:
XS GIS Cut Line= 3
      1626841.82      6809821.39      1626698.60      6810244.56
      1626497.00      6810773.49
#Sta/Elev= 30
  4557.1 1918.49  4592.2 1917.11  4597.5 1917.59  4655.1 1915.33  4680.2 1915.21
  4686.5 1914.42  4743.5 1913.50  4749.4 1912.79  4764.7 1912.83  4780.8 1911.90
  4786.1 1912.23  4875.1 1909.74  4938.0 1905.73  4954.7 1902.62  4964.1 1899.85
  4973.2 1898.96  4973.6 1898.46  4978.1 1898.46  4978.5 1898.96  4995.6 1900.26
  5000.8 1899.84  5003.0 1900.36  5025.8 1899.14  5039.6 1899.44  5050.3 1900.32
  5061.2 1903.20  5264.4 1902.84  5420.3 1907.48  5521.2 1909.71  5569.9 1910.23
#Mann=3,-1,0
  4557.1    0.05       0  4973.2    0.05       0  4978.5    0.05       0
Bank Sta=4973.2,4978.5
Exp/Cntr=0.3,0.1

Type RM Length L Ch R = 1,1668,534,534,534
BEGIN DESCRIPTION:
Elm 01 97 1667.89
END DESCRIPTION:
XS GIS Cut Line= 3
      1626188.61      6809769.33      1626114.83      6810188.13
      1626036.95      6810614.32
#Sta/Elev= 30
  4574.7 1920.14  4614.0 1918.58  4644.4 1916.10  4681.0 1914.10  4735.2 1911.74
  4740.3 1911.95  4766.3 1910.87  4794.5 1909.16  4799.5 1909.23  4806.9 1908.27
  4817.0 1907.64  4867.8 1905.00  4913.0 1902.01  4928.7 1899.40  4938.9 1897.13
  4949.1 1895.74  4972.3 1896.35  5017.5 1894.39  5017.9 1893.89  5022.4 1893.89
  5022.8 1894.39  5026.0 1895.96  5050.6 1898.25  5071.0 1898.32  5111.6 1897.67
  5132.0 1898.18  5203.1 1898.22  5233.6 1898.92  5345.5 1902.89  5433.2 1904.19
#Mann=3,-1,0
  4574.7    0.05       0  5017.5    0.05       0  5022.8    0.05       0
Bank Sta=5017.5,5022.8
Exp/Cntr=0.3,0.1

Type RM Length L Ch R = 1,1134,620,620,620
BEGIN DESCRIPTION:
Elm 01 97 1134
END DESCRIPTION:
XS GIS Cut Line= 3
      1625888.13      6809762.19      1625594.75      6810142.36
      1625554.94      6810644.38
#Sta/Elev= 30
  4522.3 1912.89  4743.2 1903.79  4793.0 1902.04  4813.9 1900.87  4820.2 1900.82
  4842.9 1899.33  4863.7 1898.41  4870.7 1897.59  4878.2 1896.19  4899.0 1894.80
  4921.2 1894.39  4942.5 1893.14  4977.8 1892.87  4984.4 1893.42  4992.3 1892.58
  5008.2 1892.31  5015.5 1891.09  5015.9 1890.59  5020.4 1890.59  5020.8 1891.09
  5038.3 1895.06  5048.3 1895.58  5098.4 1894.69  5118.5 1893.88  5208.8 1896.10
  5218.8 1896.62  5248.9 1897.06  5349.2 1899.66  5429.5 1900.77  5506.1 1900.59
#Mann=3,-1,0
  4522.3    0.05       0  5015.5    0.05       0  5020.8    0.05       0
Bank Sta=5015.5,5020.8
Exp/Cntr=0.3,0.1

Type RM Length L Ch R = 1,514,0,0,0
BEGIN DESCRIPTION:
Elm 01 97 513.724
END DESCRIPTION:
XS GIS Cut Line= 3
      1625805.03      6809587.99      1625057.17      6809894.14
      1625254.99      6811087.96
#Sta/Elev= 30
  4191.9 1912.44  4230.6 1911.28  4246.0 1909.78  4337.5 1908.40  4361.5 1906.99
  4468.3 1904.66  4883.5 1899.51  4926.7 1897.81  4991.5 1890.50  5031.6 1888.29
  5032.1 1887.79  5037.0 1888.29  5064.7 1890.62  5125.6 1890.15  5156.0 1892.24
  5196.1 1890.03  5257.1 1890.02  5328.3 1891.77  5358.7 1891.33  5368.8 1890.07
  5429.6 1893.09  5567.2 1894.84  5628.2 1894.91  5672.9 1893.65  5703.3 1894.81
  5733.7 1894.08  5750.1 1896.04  5811.1 1898.51  5938.2 1901.27  6210.1 1909.90
#Mann=3,-1,0
  4191.9    0.05       0  5031.6    0.05       0  5037.0    0.05       0
Bank Sta=5031.6,5037
Exp/Cntr=0.3,0.1

Chan Stop Cuts=-1