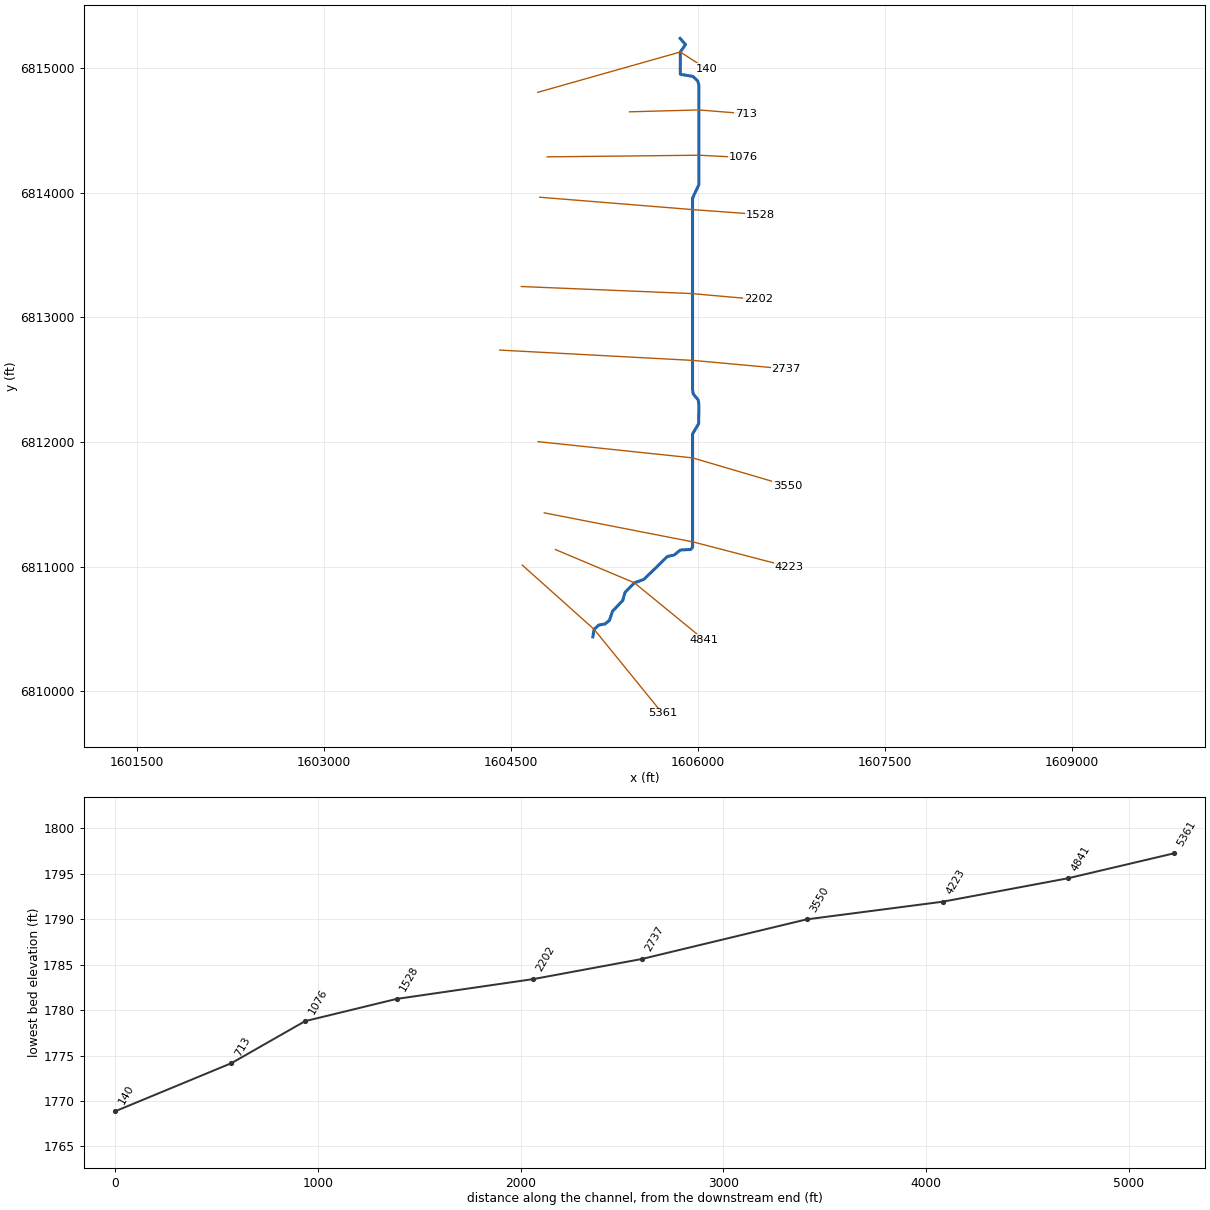
--- Elm 01 98.prj (project) ---

Proj Title=Elm 01 98 Base Level Engineering
Current Plan=p01
Default Exp/Contr=0.3,0.1
English Units
Geom File=g01
Flow File=f01
Plan File=p01
BEGIN DESCRIPTION:
Elm 01 98
END DESCRIPTION:

--- Elm 01 98.p01 (plan) ---

Plan Title=Multiple Run
Short Identifier=Multiple
Geom File=g01
Flow File=f01
Subcritical Flow
K Sum by GR= 0
Std Step Tol= 0.01
Critical Tol= 0.01
Num of Std Step Trials= 20
Max Error Tol= 0.3
Flow Tol Ratio= 0.001
Split Flow NTrial= 30
Split Flow Tol= 0.02
Split Flow Ratio= 0.02
Log Output Level= 0
Friction Slope Method= 1
Unsteady Friction Slope Method= 2
Unsteady Bridges Friction Slope Method= 1
Parabolic Critical Depth
Global Vel Dist=  1 , 1 , 1
Global Log Level= 0
CheckData=True
Encroach Param= -1, 0, 0, 0
BEGIN DESCRIPTION:
Multiple Run
END DESCRIPTION:

--- Elm 01 98.f01 (steady flow) ---

Flow Title=Multiple
Number of Profiles=7
Profile Names=10-year,25-year,50-year,1pct_min,100-year,1pct_plu,500-year
River Rch & RM= Elm 01 98,Reach-1,5361
     160     216     261     197     315     433     463
River Rch & RM= Elm 01 98,Reach-1,4841
     259     359     443     338     542     745     822
Boundary for River Rch & Prof#=Elm 01 98,Reach-1,1
Up Type=0
Dn Type=3
Dn Slope=0.001
Boundary for River Rch & Prof#=Elm 01 98,Reach-1,2
Up Type=0
Dn Type=3
Dn Slope=0.001
Boundary for River Rch & Prof#=Elm 01 98,Reach-1,3
Up Type=0
Dn Type=3
Dn Slope=0.001
Boundary for River Rch & Prof#=Elm 01 98,Reach-1,4
Up Type=0
Dn Type=3
Dn Slope=0.001
Boundary for River Rch & Prof#=Elm 01 98,Reach-1,5
Up Type=0
Dn Type=3
Dn Slope=0.001
Boundary for River Rch & Prof#=Elm 01 98,Reach-1,6
Up Type=0
Dn Type=3
Dn Slope=0.001
Boundary for River Rch & Prof#=Elm 01 98,Reach-1,7
Up Type=0
Dn Type=3
Dn Slope=0.001

--- Elm 01 98.g01 (geometry) ---

Geom Title=Existing Conditions

River Reach=Elm 01 98,Reach-1
Reach XY= 30
      1605155.00      6810438.00      1605165.33      6810498.25
      1605202.52      6810532.28      1605253.56      6810541.87
      1605288.50      6810570.95      1605313.18      6810644.02
      1605394.20      6810728.33      1605413.15      6810794.07
      1605488.29      6810871.36      1605564.68      6810898.78
      1605752.70      6811082.17      1605807.17      6811094.14
      1605856.66      6811134.14      1605940.55      6811138.89
      1605954.86      6811156.34      1605954.91      6812065.31
      1606003.62      6812147.66      1606005.46      6812297.28
      1606001.22      6812336.43      1605960.75      6812385.67
      1605954.64      6812417.85      1605954.61      6813956.34
      1606005.20      6814062.92      1606005.40      6814860.97
      1605997.32      6814894.52      1605957.65      6814932.57
      1605856.50      6814949.53      1605856.47      6815128.42
      1605898.09      6815188.14      1605855.00      6815238.00

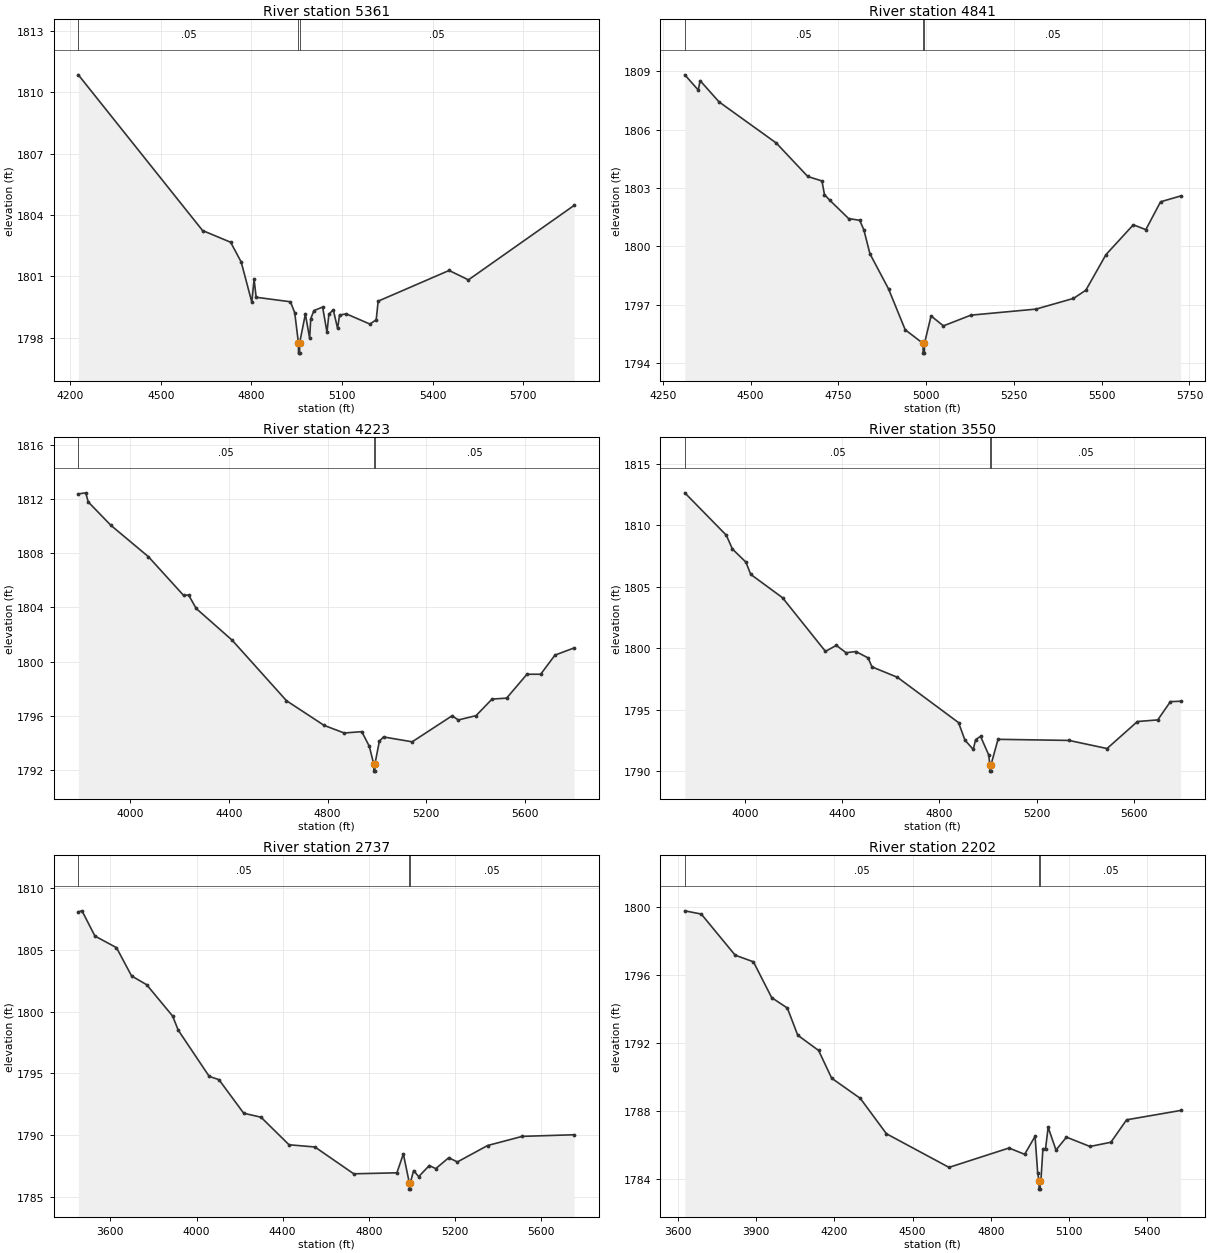
Type RM Length L Ch R = 1,5361,520,520,520
BEGIN DESCRIPTION:
Elm 01 98 5259.138
END DESCRIPTION:
XS GIS Cut Line= 3
      1604589.02      6811013.42      1605165.33      6810498.25
      1605713.15      6809824.19
#Sta/Elev= 30
  4227.0 1810.85  4638.4 1803.24  4731.2 1802.67  4766.3 1801.70  4801.4 1799.74
  4808.9 1800.86  4815.7 1799.98  4929.3 1799.76  4943.5 1799.22  4955.7 1797.75
  4956.0 1797.25  4959.5 1797.25  4959.7 1797.75  4978.7 1799.16  4992.9 1797.97
  4996.4 1798.93  5007.1 1799.33  5035.8 1799.50  5050.2 1798.27  5056.6 1799.15
  5071.0 1799.37  5085.4 1798.46  5091.8 1799.11  5114.1 1799.17  5192.4 1798.67
  5213.2 1798.88  5219.7 1799.79  5454.6 1801.29  5518.5 1800.83  5868.6 1804.47
#Mann=3,-1,0
  4227.0    0.05       0  4955.7    0.05       0  4959.7    0.05       0
Bank Sta=4955.7,4959.7
Exp/Cntr=0.3,0.1

Type RM Length L Ch R = 1,4841,618,618,618
BEGIN DESCRIPTION:
Elm 01 98 4291.443
END DESCRIPTION:
XS GIS Cut Line= 3
      1604855.03      6811137.99      1605488.29      6810871.36
      1606049.27      6810412.40
#Sta/Elev= 30
  4312.9 1808.81  4351.2 1808.03  4356.6 1808.51  4410.5 1807.42  4573.3 1805.31
  4663.1 1803.59  4703.5 1803.36  4710.6 1802.66  4725.2 1802.38  4779.4 1801.43
  4811.0 1801.34  4822.8 1800.85  4840.1 1799.62  4893.0 1797.82  4940.5 1795.72
  4991.3 1795.02  4991.6 1794.52  4995.2 1794.52  4995.4 1795.02  5014.2 1796.43
  5049.3 1795.92  5127.6 1796.47  5312.8 1796.78  5419.7 1797.33  5454.9 1797.75
  5512.3 1799.58  5590.1 1801.11  5625.7 1800.86  5667.6 1802.29  5724.8 1802.59
#Mann=3,-1,0
  4312.9    0.05       0  4991.3    0.05       0  4995.4    0.05       0
Bank Sta=4991.3,4995.4
Exp/Cntr=0.3,0.1

Type RM Length L Ch R = 1,4223,673,673,673
BEGIN DESCRIPTION:
Elm 01 98 4223.24
END DESCRIPTION:
XS GIS Cut Line= 3
      1604765.54      6811432.42      1605956.52      6811199.78
      1606730.39      6810998.50
#Sta/Elev= 30
  3788.2 1812.37  3818.2 1812.45  3828.4 1811.78  3920.1 1810.06  4072.9 1807.74
  4215.6 1804.89  4236.0 1804.92  4266.5 1803.93  4412.7 1801.59  4633.3 1797.13
  4786.2 1795.31  4867.7 1794.75  4939.0 1794.85  4969.6 1793.77  4987.9 1792.44
  4988.2 1791.94  4991.8 1791.94  4992.1 1792.44  5010.5 1794.15  5027.3 1794.46
  5143.7 1794.10  5305.8 1796.02  5330.8 1795.71  5403.1 1796.03  5467.9 1797.25
  5527.1 1797.32  5609.7 1799.08  5665.4 1799.08  5723.4 1800.49  5801.3 1801.02
#Mann=3,-1,0
  3788.2    0.05       0  4987.9    0.05       0  4992.1    0.05       0
Bank Sta=4987.9,4992.1
Exp/Cntr=0.3,0.1

Type RM Length L Ch R = 1,3550,813,813,813
BEGIN DESCRIPTION:
Elm 01 98 3550.04
END DESCRIPTION:
XS GIS Cut Line= 3
      1604715.32      6812003.50      1605954.92      6811873.29
      1606715.30      6811649.34
#Sta/Elev= 30
  3753.6 1812.65  3924.2 1809.20  3949.6 1808.07  4004.7 1807.01  4024.8 1806.01
  4155.5 1804.11  4332.1 1799.74  4376.7 1800.23  4416.9 1799.63  4457.1 1799.73
  4507.4 1799.21  4523.3 1798.48  4628.1 1797.63  4879.4 1793.94  4905.8 1792.51
  4939.8 1791.76  4949.8 1792.56  4969.9 1792.82  5003.2 1791.32  5008.4 1790.49
  5008.7 1789.99  5012.4 1789.99  5012.6 1790.49  5041.8 1792.58  5333.7 1792.49
  5490.1 1791.83  5615.2 1794.03  5698.6 1794.16  5750.7 1795.65  5792.7 1795.68
#Mann=3,-1,0
  3753.6    0.05       0  5008.4    0.05       0  5012.6    0.05       0
Bank Sta=5008.4,5012.6
Exp/Cntr=0.3,0.1

Type RM Length L Ch R = 1,2737,535,535,535
BEGIN DESCRIPTION:
Elm 01 98 2737.09
END DESCRIPTION:
XS GIS Cut Line= 3
      1604408.05      6812737.87      1605965.33      6812654.54
      1606704.93      6812586.83
#Sta/Elev= 30
  3451.2 1808.07  3468.2 1808.15  3528.3 1806.11  3628.4 1805.17  3698.5 1802.88
  3768.6 1802.17  3888.8 1799.64  3915.2 1798.49  4059.0 1794.75  4104.0 1794.49
  4219.2 1791.77  4299.4 1791.45  4429.5 1789.22  4549.7 1789.04  4730.0 1786.87
  4930.3 1786.95  4960.3 1788.48  4988.1 1786.13  4988.4 1785.63  4992.2 1785.63
  4992.5 1786.13  5008.0 1787.13  5031.5 1786.64  5080.7 1787.54  5110.8 1787.29
  5171.0 1788.17  5211.2 1787.83  5351.7 1789.16  5512.5 1789.90  5753.4 1790.03
#Mann=3,-1,0
  3451.2    0.05       0  4988.1    0.05       0  4992.5    0.05       0
Bank Sta=4988.1,4992.5
Exp/Cntr=0.3,0.1

Type RM Length L Ch R = 1,2202,674,674,674
BEGIN DESCRIPTION:
Elm 01 98 2201.91
END DESCRIPTION:
XS GIS Cut Line= 3
      1604581.83      6813247.60      1605944.64      6813191.18
      1606481.46      6813143.56
#Sta/Elev= 30
  3626.0 1799.80  3689.2 1799.61  3819.3 1797.19  3889.4 1796.80  3959.5 1794.69
  4019.5 1794.08  4059.5 1792.48  4139.6 1791.58  4189.6 1789.95  4299.7 1788.76
  4399.8 1786.68  4640.0 1784.70  4870.2 1785.84  4930.3 1785.47  4970.3 1786.53
  4980.3 1784.38  4985.5 1783.92  4985.8 1783.42  4989.6 1783.42  4989.9 1783.92
  4992.7 1783.92  5000.4 1785.80  5010.4 1785.79  5020.5 1787.06  5050.6 1785.72
  5090.7 1786.48  5181.1 1785.93  5261.4 1786.18  5321.6 1787.50  5528.9 1788.05
#Mann=3,-1,0
  3626.0    0.05       0  4985.5    0.05       0  4989.9    0.05       0
Bank Sta=4985.5,4989.9
Exp/Cntr=0.3,0.1

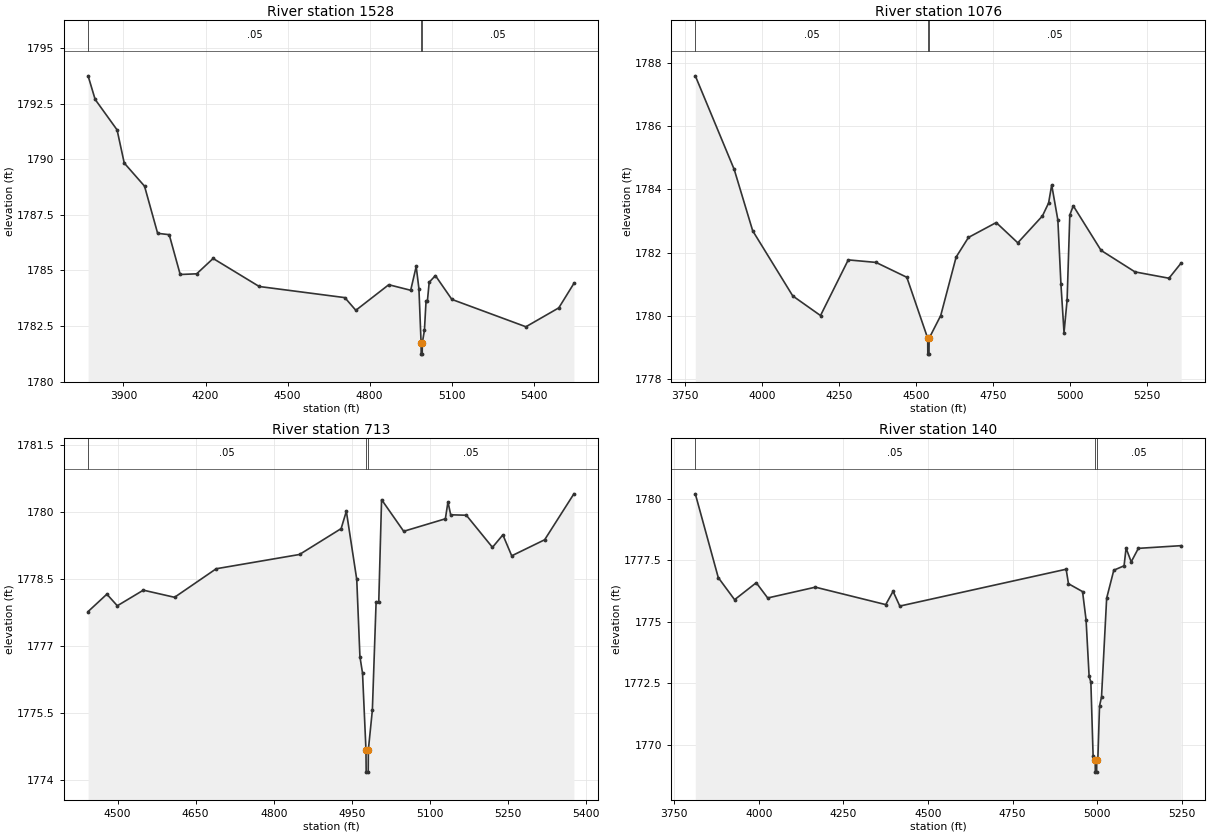
Type RM Length L Ch R = 1,1528,452,452,452
BEGIN DESCRIPTION:
Elm 01 98 1527.69
END DESCRIPTION:
XS GIS Cut Line= 3
      1604729.32      6813963.75      1605962.00      6813863.92
      1606500.07      6813824.87
#Sta/Elev= 30
  3770.7 1793.75  3796.5 1792.69  3876.7 1791.32  3902.9 1789.83  3977.1 1788.79
  4025.0 1786.67  4067.3 1786.61  4107.5 1784.82  4167.7 1784.85  4227.9 1785.54
  4396.4 1784.28  4709.4 1783.78  4749.6 1783.21  4870.0 1784.36  4950.2 1784.11
  4970.3 1785.18  4980.3 1784.18  4988.2 1781.74  4988.5 1781.24  4992.3 1781.24
  4992.6 1781.74  5000.4 1782.31  5006.4 1783.64  5011.4 1783.64  5017.8 1784.47
  5040.5 1784.77  5100.7 1783.70  5371.4 1782.47  5491.7 1783.32  5546.9 1784.42
#Mann=3,-1,0
  3770.7    0.05       0  4988.2    0.05       0  4992.6    0.05       0
Bank Sta=4988.2,4992.6
Exp/Cntr=0.3,0.1

Type RM Length L Ch R = 1,1076,363,363,363
BEGIN DESCRIPTION:
Elm 01 98 1076.25
END DESCRIPTION:
XS GIS Cut Line= 3
      1604788.83      6814287.53      1606007.58      6814300.56
      1606364.40      6814282.32
#Sta/Elev= 30
  3783.5 1787.59  3909.7 1784.63  3969.7 1782.69  4099.7 1780.63  4189.7 1780.01
  4279.7 1781.77  4369.7 1781.69  4469.7 1781.22  4537.5 1779.29  4537.8 1778.79
  4541.6 1778.79  4542.0 1779.29  4579.7 1780.01  4629.7 1781.86  4669.7 1782.48
  4759.7 1782.95  4829.7 1782.31  4909.7 1783.16  4929.7 1783.57  4939.7 1784.14
  4959.7 1783.03  4969.7 1781.00  4979.7 1779.47  4989.7 1780.50  4998.5 1783.19
  5009.7 1783.48  5099.9 1782.07  5210.0 1781.39  5320.2 1781.19  5359.6 1781.67
#Mann=3,-1,0
  3783.5    0.05       0  4537.5    0.05       0  4542.0    0.05       0
Bank Sta=4537.5,4542
Exp/Cntr=0.3,0.1

Type RM Length L Ch R = 1,713,573,573,573
BEGIN DESCRIPTION:
Elm 01 98 712.98
END DESCRIPTION:
XS GIS Cut Line= 3
      1605448.86      6814648.69      1606004.41      6814663.88
      1606381.04      6814633.58
#Sta/Elev= 30
  4443.3 1777.77  4479.4 1778.16  4499.5 1777.90  4549.5 1778.25  4609.5 1778.09
  4689.5 1778.73  4849.6 1779.05  4929.6 1779.63  4939.6 1780.02  4959.6 1778.49
  4965.7 1776.76  4970.7 1776.39  4977.3 1774.67  4977.7 1774.17  4981.6 1774.17
  4981.9 1774.67  4989.6 1775.56  4996.8 1777.99  5001.9 1777.99  5007.3 1780.28
  5049.8 1779.57  5129.9 1779.85  5134.9 1780.23  5140.1 1779.94  5170.2 1779.93
  5220.4 1779.21  5240.4 1779.49  5257.4 1779.02  5320.7 1779.38  5376.9 1780.41
#Mann=3,-1,0
  4443.3    0.05       0  4977.3    0.05       0  4981.9    0.05       0
Bank Sta=4977.3,4981.9
Exp/Cntr=0.3,0.1

Type RM Length L Ch R = 1,140,0,0,0
BEGIN DESCRIPTION:
Elm 01 98 3812.514
END DESCRIPTION:
XS GIS Cut Line= 3
      1604713.15      6814804.93      1605856.47      6815128.42
      1606065.19      6814993.73
#Sta/Elev= 30
  3811.8 1780.21  3879.7 1776.80  3928.0 1775.90  3992.0 1776.59  4025.9 1775.97
  4166.9 1776.41  4374.9 1775.70  4396.6 1776.24  4416.5 1775.64  4908.4 1777.14
  4915.3 1776.55  4956.9 1776.23  4967.3 1775.08  4976.3 1772.79  4981.5 1772.54
  4988.1 1769.55  4994.3 1769.38  4994.7 1768.88  4998.6 1768.88  4998.9 1769.38
  5002.1 1769.38  5007.1 1771.57  5013.0 1771.94  5028.2 1775.96  5049.3 1777.10
  5079.7 1777.28  5085.6 1778.00  5100.8 1777.44  5121.9 1777.99  5248.4 1778.10
#Mann=3,-1,0
  3811.8    0.05       0  4994.3    0.05       0  4998.9    0.05       0
Bank Sta=4994.3,4998.9
Exp/Cntr=0.3,0.1

Chan Stop Cuts=-1