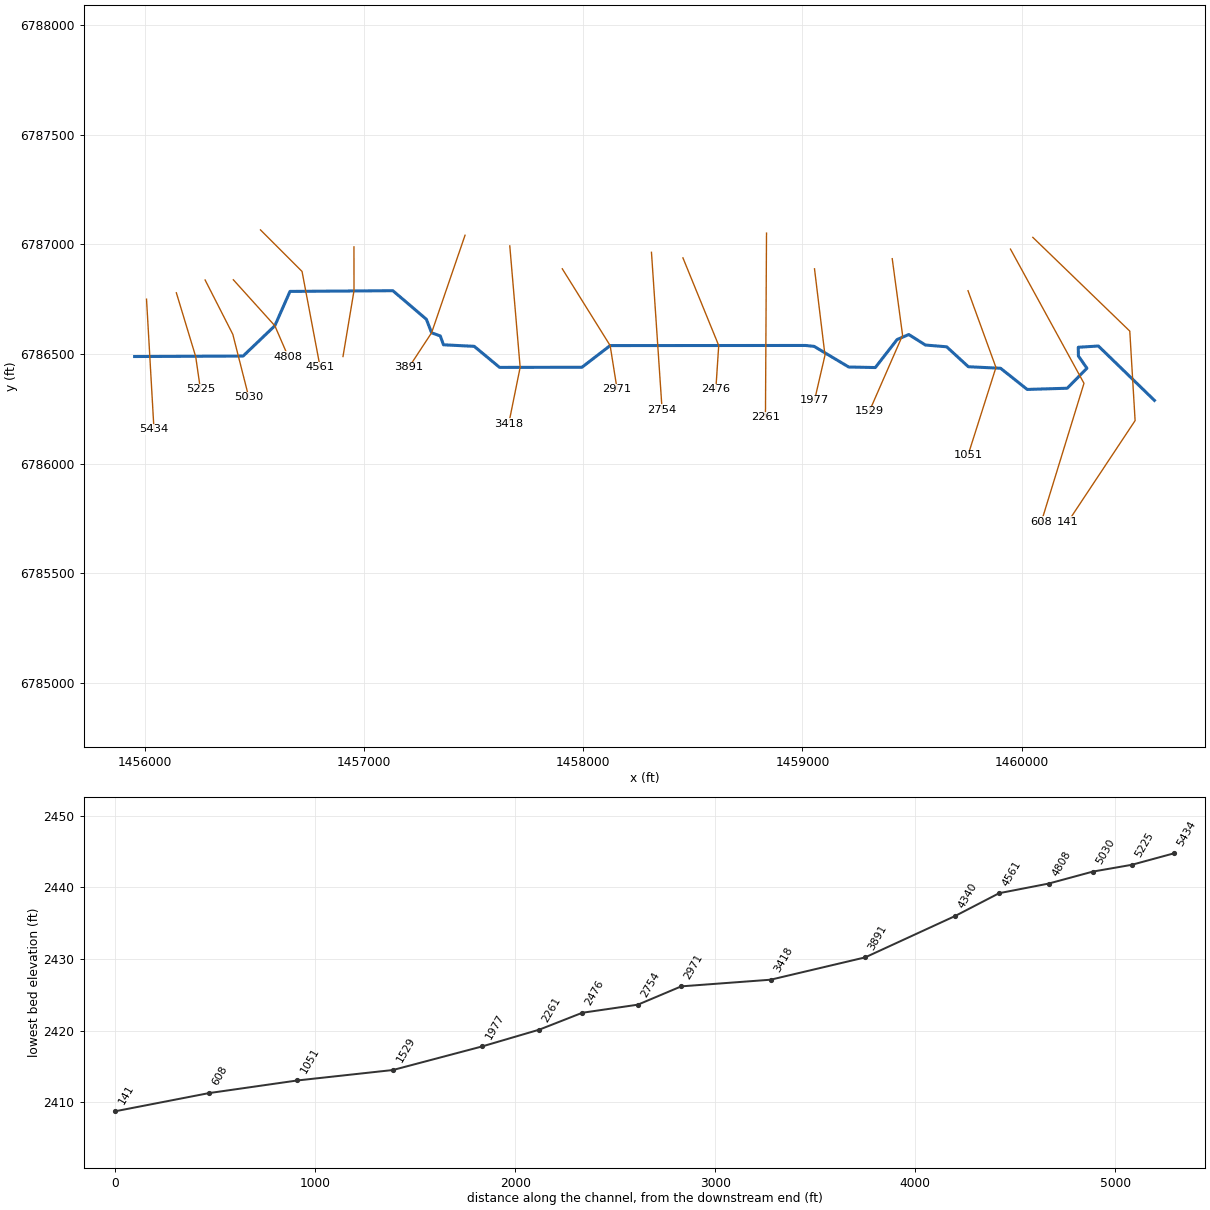
--- Elm 02.prj (project) ---

Proj Title=Elm 02 Base Level Engineering
Current Plan=p01
Default Exp/Contr=0.3,0.1
English Units
Geom File=g01
Flow File=f01
Plan File=p01
BEGIN DESCRIPTION:
Elm 02
END DESCRIPTION:

--- Elm 02.p01 (plan) ---

Plan Title=Multiple Run
Short Identifier=Multiple
Geom File=g01
Flow File=f01
Subcritical Flow
K Sum by GR= 0
Std Step Tol= 0.01
Critical Tol= 0.01
Num of Std Step Trials= 20
Max Error Tol= 0.3
Flow Tol Ratio= 0.001
Split Flow NTrial= 30
Split Flow Tol= 0.02
Split Flow Ratio= 0.02
Log Output Level= 0
Friction Slope Method= 1
Unsteady Friction Slope Method= 2
Unsteady Bridges Friction Slope Method= 1
Parabolic Critical Depth
Global Vel Dist=  1 , 1 , 1
Global Log Level= 0
CheckData=True
Encroach Param= -1, 0, 0, 0
BEGIN DESCRIPTION:
Multiple Run
END DESCRIPTION:

--- Elm 02.f01 (steady flow) ---

Flow Title=Multiple
Number of Profiles=7
Profile Names=10-year,25-year,50-year,1pct_min,100-year,1pct_plu,500-year
River Rch & RM= Elm 02,Reach-1,5434
     256     356     438     334     536     737     810
River Rch & RM= Elm 02,Reach-1,4561
     317     445     552     424     680     935    1040
Boundary for River Rch & Prof#=Elm 02,Reach-1,1
Up Type=0
Dn Type=3
Dn Slope=0.005
Boundary for River Rch & Prof#=Elm 02,Reach-1,2
Up Type=0
Dn Type=3
Dn Slope=0.005
Boundary for River Rch & Prof#=Elm 02,Reach-1,3
Up Type=0
Dn Type=3
Dn Slope=0.005
Boundary for River Rch & Prof#=Elm 02,Reach-1,4
Up Type=0
Dn Type=3
Dn Slope=0.005
Boundary for River Rch & Prof#=Elm 02,Reach-1,5
Up Type=0
Dn Type=3
Dn Slope=0.005
Boundary for River Rch & Prof#=Elm 02,Reach-1,6
Up Type=0
Dn Type=3
Dn Slope=0.005
Boundary for River Rch & Prof#=Elm 02,Reach-1,7
Up Type=0
Dn Type=3
Dn Slope=0.005

--- Elm 02.g01 (geometry) ---

Geom Title=Existing Conditions

River Reach=Elm 02,Reach-1
Reach XY= 30
      1455955.00      6786488.00      1456449.56      6786490.17
      1456594.24      6786628.32      1456663.28      6786784.94
      1457132.35      6786788.20      1457285.16      6786657.93
      1457309.01      6786596.28      1457348.83      6786581.79
      1457363.09      6786541.55      1457503.52      6786534.44
      1457618.86      6786438.54      1457994.56      6786439.06
      1458123.22      6786537.91      1459014.28      6786538.45
      1459053.45      6786534.25      1459210.94      6786440.22
      1459332.31      6786437.79      1459431.48      6786565.31
      1459484.79      6786588.36      1459560.97      6786540.38
      1459657.42      6786532.46      1459756.47      6786441.56
      1459903.53      6786434.44      1460024.99      6786337.96
      1460207.48      6786343.46      1460297.18      6786434.60
      1460258.41      6786490.09      1460257.70      6786530.26
      1460349.41      6786535.96      1460605.00      6786288.00

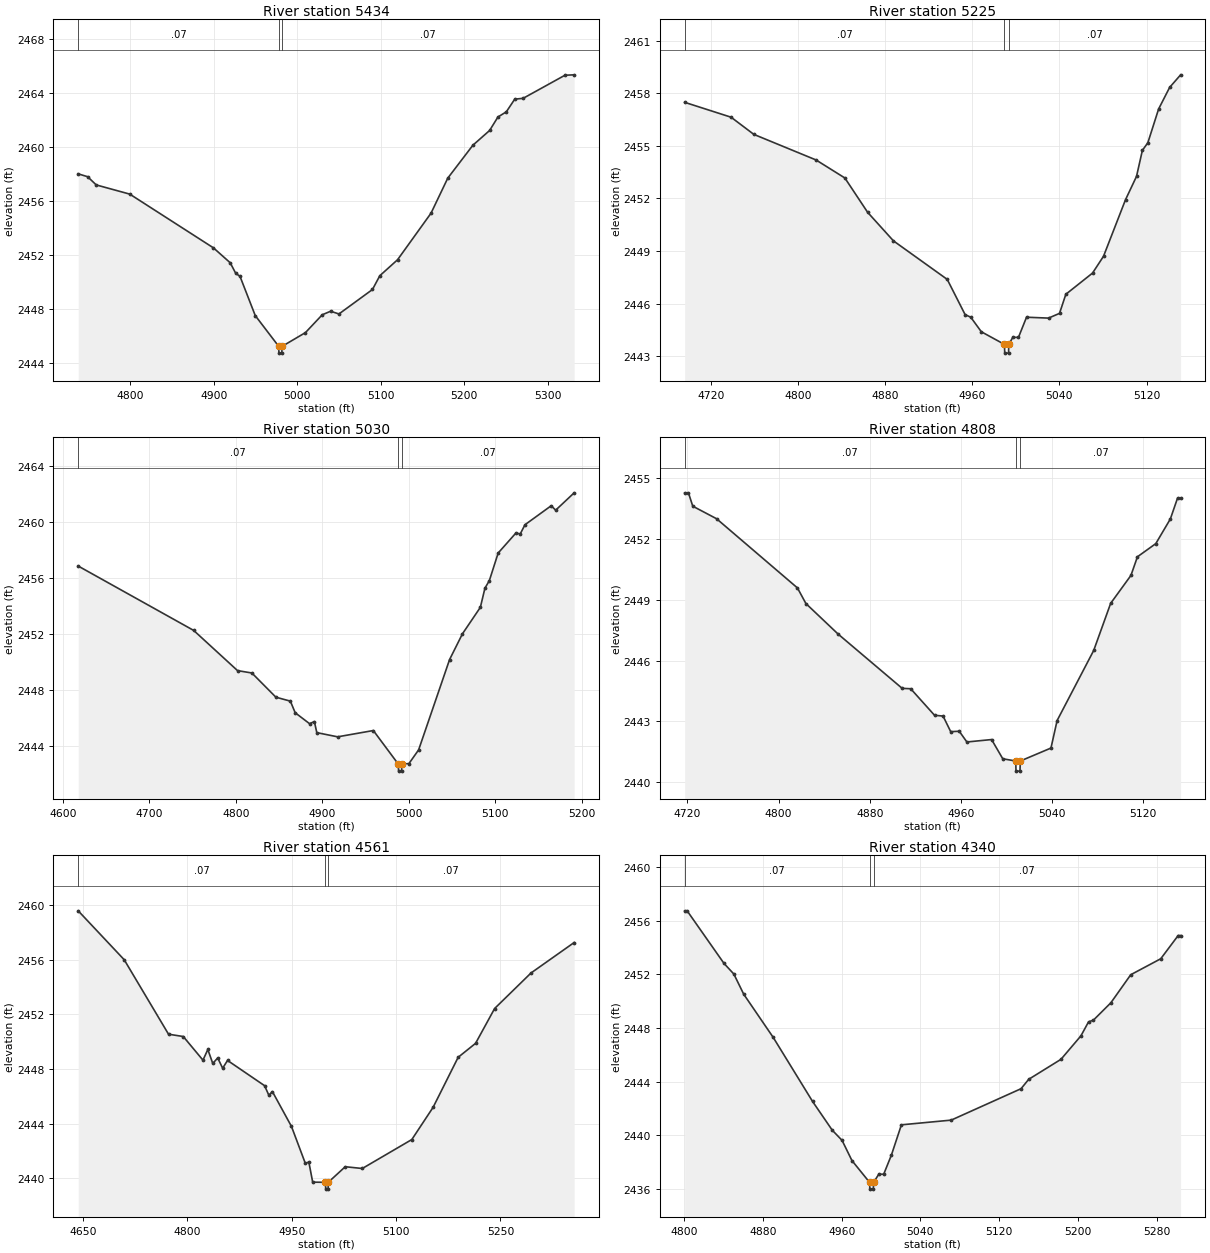
Type RM Length L Ch R = 1,5434,209,209,209
BEGIN DESCRIPTION:
elmc226
END DESCRIPTION:
XS GIS Cut Line= 2
      1456009.10      6786749.60      1456043.10      6786156.97
#Sta/Elev= 30
  4737.9 2458.03  4749.1 2457.82  4759.5 2457.21  4799.6 2456.53  4899.8 2452.55
  4919.8 2451.45  4926.5 2450.66  4931.5 2450.45  4949.8 2447.54  4977.9 2445.26
  4978.1 2444.76  4981.6 2444.76  4981.9 2445.26  5009.9 2446.28  5030.0 2447.60
  5040.0 2447.86  5050.0 2447.66  5090.1 2449.47  5098.9 2450.49  5120.1 2451.67
  5160.2 2455.12  5180.2 2457.71  5210.3 2460.15  5230.3 2461.24  5240.3 2462.24
  5250.3 2462.62  5260.4 2463.56  5270.4 2463.62  5320.5 2465.33  5331.5 2465.36
#Mann=3,-1,0
  4737.9    0.07       0  4977.9    0.07       0  4981.9    0.07       0
Bank Sta=4977.9,4981.9
Exp/Cntr=0.3,0.1

Type RM Length L Ch R = 1,5225,195,195,195
BEGIN DESCRIPTION:
elmc145
END DESCRIPTION:
XS GIS Cut Line= 3
      1456145.12      6786778.73      1456233.31      6786487.70
      1456255.01      6786337.97
#Sta/Elev= 30
  4695.9 2457.49  4738.5 2456.64  4759.4 2455.66  4816.5 2454.20  4843.0 2453.17
  4863.9 2451.21  4887.6 2449.58  4937.0 2447.38  4953.4 2445.37  4958.6 2445.22
  4968.3 2444.39  4989.5 2443.67  4989.8 2443.17  4993.3 2443.17  4993.5 2443.67
  4997.2 2444.07  5002.4 2444.07  5009.8 2445.22  5030.0 2445.17  5040.1 2445.44
  5045.9 2446.53  5070.4 2447.74  5080.5 2448.70  5100.7 2451.93  5110.8 2453.26
  5116.2 2454.75  5121.2 2455.18  5131.1 2457.11  5141.2 2458.34  5151.3 2459.06
#Mann=3,-1,0
  4695.9    0.07       0  4989.5    0.07       0  4993.5    0.07       0
Bank Sta=4989.5,4993.5
Exp/Cntr=0.3,0.1

Type RM Length L Ch R = 1,5030,222,222,222
BEGIN DESCRIPTION:
elmc225
END DESCRIPTION:
XS GIS Cut Line= 3
      1456276.26      6786837.07      1456402.56      6786589.32
      1456475.40      6786302.82
#Sta/Elev= 30
  4617.7 2456.87  4751.3 2452.27  4802.0 2449.40  4818.6 2449.23  4846.4 2447.50
  4863.1 2447.22  4868.7 2446.39  4885.3 2445.61  4890.9 2445.76  4893.7 2444.97
  4917.8 2444.67  4959.1 2445.12  4988.0 2442.72  4988.3 2442.22  4991.8 2442.22
  4992.0 2442.72  5000.3 2442.76  5011.5 2443.74  5047.3 2450.19  5062.2 2452.03
  5082.9 2453.92  5088.2 2455.29  5093.3 2455.83  5103.5 2457.80  5123.9 2459.22
  5129.1 2459.17  5134.5 2459.82  5164.9 2461.18  5170.0 2460.86  5191.4 2462.10
#Mann=3,-1,0
  4617.7    0.07       0  4988.0    0.07       0  4992.0    0.07       0
Bank Sta=4988,4992
Exp/Cntr=0.3,0.1

Type RM Length L Ch R = 1,4808,247,247,247
BEGIN DESCRIPTION:
elmc144
END DESCRIPTION:
XS GIS Cut Line= 3
      1456405.03      6786837.96      1456594.24      6786628.32
      1456655.00      6786488.01
#Sta/Elev= 30
  4717.6 2454.29  4720.9 2454.29  4724.7 2453.63  4745.6 2453.01  4816.6 2449.59
  4824.0 2448.82  4852.3 2447.31  4908.5 2444.63  4916.0 2444.61  4936.9 2443.30
  4944.4 2443.26  4951.1 2442.49  4958.6 2442.51  4965.3 2441.98  4987.0 2442.10
  4996.8 2441.15  5008.2 2441.04  5008.4 2440.54  5011.9 2440.54  5012.2 2441.04
  5039.1 2441.68  5044.5 2443.04  5076.6 2446.50  5091.5 2448.83  5109.3 2450.21
  5115.0 2451.13  5131.1 2451.78  5143.9 2453.00  5150.2 2454.03  5152.9 2454.03
#Mann=3,-1,0
  4717.6    0.07       0  5008.2    0.07       0  5012.2    0.07       0
Bank Sta=5008.2,5012.2
Exp/Cntr=0.3,0.1

Type RM Length L Ch R = 1,4561,221,221,221
BEGIN DESCRIPTION:
elmc224
END DESCRIPTION:
XS GIS Cut Line= 3
      1456528.84      6787065.37      1456718.30      6786875.92
      1456800.87      6786438.78
#Sta/Elev= 30
  4643.2 2459.57  4709.3 2455.99  4773.0 2450.54  4794.2 2450.37  4822.5 2448.64
  4829.5 2449.42  4836.6 2448.40  4843.7 2448.80  4850.8 2448.05  4857.8 2448.62
  4911.1 2446.77  4917.2 2446.07  4922.3 2446.34  4949.7 2443.79  4969.6 2441.09
  4974.7 2441.18  4980.2 2439.71  4998.6 2439.70  4998.9 2439.20  5002.4 2439.20
  5002.6 2439.70  5027.0 2440.84  5051.5 2440.71  5122.7 2442.83  5153.3 2445.19
  5189.3 2448.85  5214.3 2449.87  5241.7 2452.42  5294.0 2455.02  5356.0 2457.25
#Mann=3,-1,0
  4643.2    0.07       0  4998.6    0.07       0  5002.6    0.07       0
Bank Sta=4998.6,5002.6
Exp/Cntr=0.3,0.1

Type RM Length L Ch R = 1,4340,449,449,449
BEGIN DESCRIPTION:
elmc143
END DESCRIPTION:
XS GIS Cut Line= 3
      1456955.00      6786987.97      1456955.19      6786788.37
      1456905.01      6786488.04
#Sta/Elev= 30
  4800.4 2456.73  4802.9 2456.73  4840.4 2452.81  4850.4 2452.02  4860.4 2450.52
  4890.4 2447.30  4930.4 2442.53  4950.4 2440.39  4960.4 2439.63  4970.4 2438.13
  4988.4 2436.50  4988.6 2436.00  4992.1 2436.00  4992.4 2436.50  4997.7 2437.11
  5002.7 2437.11  5010.5 2438.53  5020.7 2440.79  5071.3 2441.14  5142.3 2443.48
  5150.1 2444.18  5182.9 2445.67  5203.2 2447.42  5210.9 2448.46  5215.9 2448.59
  5233.6 2449.88  5253.8 2451.97  5284.3 2453.16  5302.0 2454.89  5304.5 2454.89
#Mann=3,-1,0
  4800.4    0.07       0  4988.4    0.07       0  4992.4    0.07       0
Bank Sta=4988.4,4992.4
Exp/Cntr=0.3,0.1

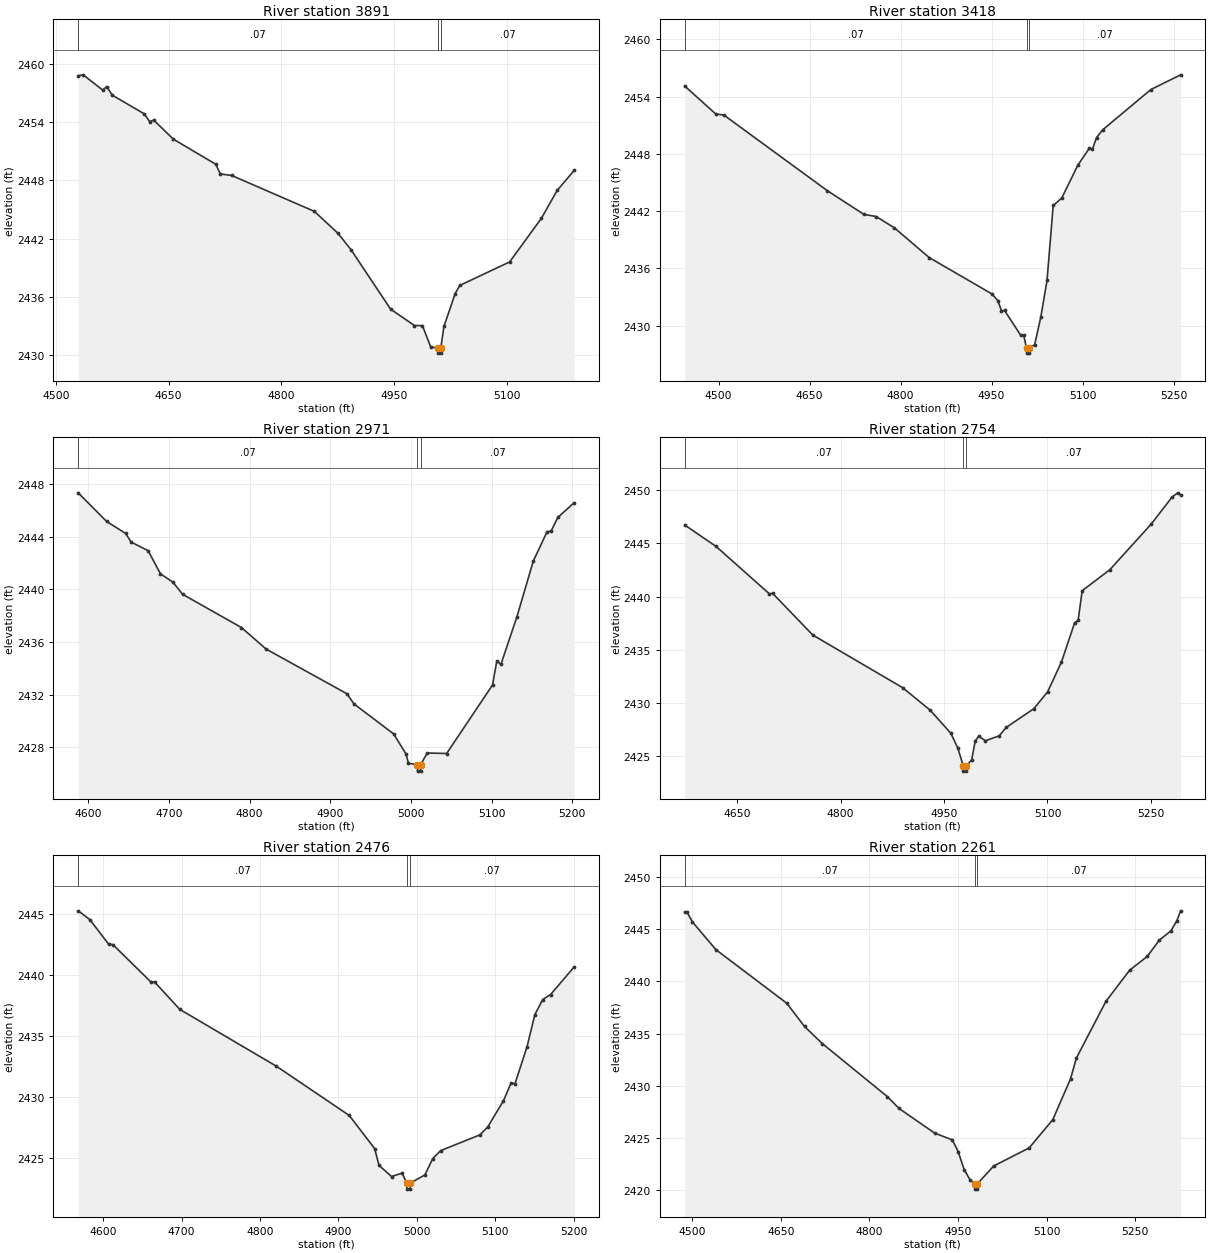
Type RM Length L Ch R = 1,3891,473,473,473
BEGIN DESCRIPTION:
elmc142
END DESCRIPTION:
XS GIS Cut Line= 3
      1457461.50      6787041.07      1457309.01      6786596.28
      1457205.00      6786438.00
#Sta/Elev= 30
  4529.8 2458.76  4536.4 2458.85  4562.4 2457.28  4567.7 2457.64  4575.3 2456.75
  4617.6 2454.84  4624.9 2454.03  4630.2 2454.20  4656.2 2452.24  4712.8 2449.65
  4718.7 2448.66  4733.9 2448.50  4843.8 2444.81  4875.1 2442.57  4892.5 2440.88
  4945.3 2434.75  4977.0 2433.07  4987.6 2433.06  4998.5 2430.89  5007.9 2430.73
  5008.2 2430.23  5011.7 2430.23  5012.0 2430.73  5016.2 2432.97  5031.2 2436.36
  5037.2 2437.19  5103.6 2439.61  5145.7 2444.08  5166.8 2446.96  5189.4 2449.02
#Mann=3,-1,0
  4529.8    0.07       0  5007.9    0.07       0  5012.0    0.07       0
Bank Sta=5007.9,5012
Exp/Cntr=0.3,0.1

Type RM Length L Ch R = 1,3418,447,447,447
BEGIN DESCRIPTION:
elmc141
END DESCRIPTION:
XS GIS Cut Line= 3
      1457665.52      6786992.46      1457712.79      6786438.67
      1457660.84      6786182.18
#Sta/Elev= 30
  4444.2 2455.11  4495.3 2452.18  4508.9 2452.06  4679.5 2444.13  4739.7 2441.65
  4759.8 2441.43  4789.9 2440.24  4847.4 2437.12  4950.5 2433.32  4960.5 2432.61
  4966.4 2431.53  4971.4 2431.59  4997.8 2429.01  5002.9 2429.01  5007.8 2427.61
  5008.1 2427.11  5011.7 2427.11  5012.0 2427.61  5021.1 2428.00  5031.3 2430.91
  5041.5 2434.74  5051.7 2442.59  5065.7 2443.36  5092.5 2446.83  5111.3 2448.59
  5116.4 2448.50  5123.1 2449.70  5133.3 2450.52  5212.7 2454.74  5261.7 2456.28
#Mann=3,-1,0
  4444.2    0.07       0  5007.8    0.07       0  5012.0    0.07       0
Bank Sta=5007.8,5012
Exp/Cntr=0.3,0.1

Type RM Length L Ch R = 1,2971,217,217,217
BEGIN DESCRIPTION:
elmc140
END DESCRIPTION:
XS GIS Cut Line= 3
      1457905.02      6786887.97      1458123.22      6786537.91
      1458155.00      6786338.02
#Sta/Elev= 30
  4587.5 2447.34  4622.8 2445.16  4646.4 2444.25  4653.0 2443.60  4674.2 2442.94
  4689.5 2441.18  4704.9 2440.55  4717.1 2439.62  4789.8 2437.10  4820.5 2435.46
  4920.8 2432.06  4929.2 2431.30  4978.6 2429.01  4994.0 2427.48  4997.0 2426.77
  5007.9 2426.68  5008.2 2426.18  5011.9 2426.18  5012.2 2426.68  5020.2 2427.56
  5044.3 2427.52  5101.2 2432.73  5106.5 2434.55  5111.6 2434.29  5131.5 2437.93
  5151.8 2442.16  5168.8 2444.38  5173.8 2444.43  5182.2 2445.47  5202.4 2446.59
#Mann=3,-1,0
  4587.5    0.07       0  5007.9    0.07       0  5012.2    0.07       0
Bank Sta=5007.9,5012.2
Exp/Cntr=0.3,0.1

Type RM Length L Ch R = 1,2754,278,278,278
BEGIN DESCRIPTION:
elmc223
END DESCRIPTION:
XS GIS Cut Line= 2
      1458311.57      6786963.37      1458360.08      6786245.51
#Sta/Elev= 30
  4573.7 2446.73  4619.2 2444.72  4696.5 2440.27  4701.5 2440.30  4759.5 2436.40
  4889.8 2431.46  4929.9 2429.34  4959.9 2427.17  4970.0 2425.78  4977.8 2424.12
  4978.1 2423.62  4981.9 2423.62  4982.2 2424.12  4990.0 2424.66  4995.2 2426.45
  5000.2 2426.89  5010.1 2426.47  5030.1 2426.94  5040.1 2427.72  5080.2 2429.48
  5100.3 2431.07  5120.3 2433.86  5139.5 2437.56  5144.5 2437.77  5150.4 2440.56
  5190.5 2442.53  5250.6 2446.82  5280.7 2449.34  5288.9 2449.75  5293.2 2449.57
#Mann=3,-1,0
  4573.7    0.07       0  4977.8    0.07       0  4982.2    0.07       0
Bank Sta=4977.8,4982.2
Exp/Cntr=0.3,0.1

Type RM Length L Ch R = 1,2476,215,215,215
BEGIN DESCRIPTION:
elmc139
END DESCRIPTION:
XS GIS Cut Line= 3
      1458455.01      6786937.97      1458618.25      6786538.21
      1458605.00      6786338.05
#Sta/Elev= 30
  4568.2 2445.27  4582.9 2444.56  4606.9 2442.55  4612.3 2442.51  4660.4 2439.48
  4665.8 2439.43  4697.8 2437.20  4820.7 2432.56  4913.8 2428.52  4946.2 2425.81
  4951.7 2424.44  4967.8 2423.52  4981.1 2423.80  4987.2 2422.99  4987.5 2422.49
  4991.4 2422.49  4991.7 2422.99  5010.2 2423.65  5020.3 2424.99  5030.3 2425.64
  5080.4 2426.93  5090.4 2427.58  5110.5 2429.73  5120.2 2431.18  5125.2 2431.12
  5140.5 2434.14  5150.5 2436.78  5160.6 2438.01  5170.6 2438.42  5200.6 2440.68
#Mann=3,-1,0
  4568.2    0.07       0  4987.2    0.07       0  4991.7    0.07       0
Bank Sta=4987.2,4991.7
Exp/Cntr=0.3,0.1

Type RM Length L Ch R = 1,2261,284,284,284
BEGIN DESCRIPTION:
elmc222
END DESCRIPTION:
XS GIS Cut Line= 2
      1458836.19      6787050.83      1458831.34      6786211.75
#Sta/Elev= 30
  4487.5 2446.64  4491.4 2446.64  4500.3 2445.70  4540.3 2443.03  4660.3 2437.90
  4690.3 2435.68  4720.3 2434.05  4830.3 2428.98  4850.3 2427.84  4910.3 2425.49
  4940.3 2424.84  4950.3 2423.71  4960.3 2422.00  4970.3 2421.02  4978.1 2420.63
  4978.4 2420.13  4982.3 2420.13  4982.6 2420.63  5010.3 2422.34  5070.3 2424.07
  5110.3 2426.77  5140.3 2430.67  5150.3 2432.67  5200.3 2438.09  5240.3 2441.06
  5270.3 2442.39  5290.3 2443.92  5310.3 2444.83  5320.3 2445.81  5326.6 2446.74
#Mann=3,-1,0
  4487.5    0.07       0  4978.1    0.07       0  4982.6    0.07       0
Bank Sta=4978.1,4982.6
Exp/Cntr=0.3,0.1

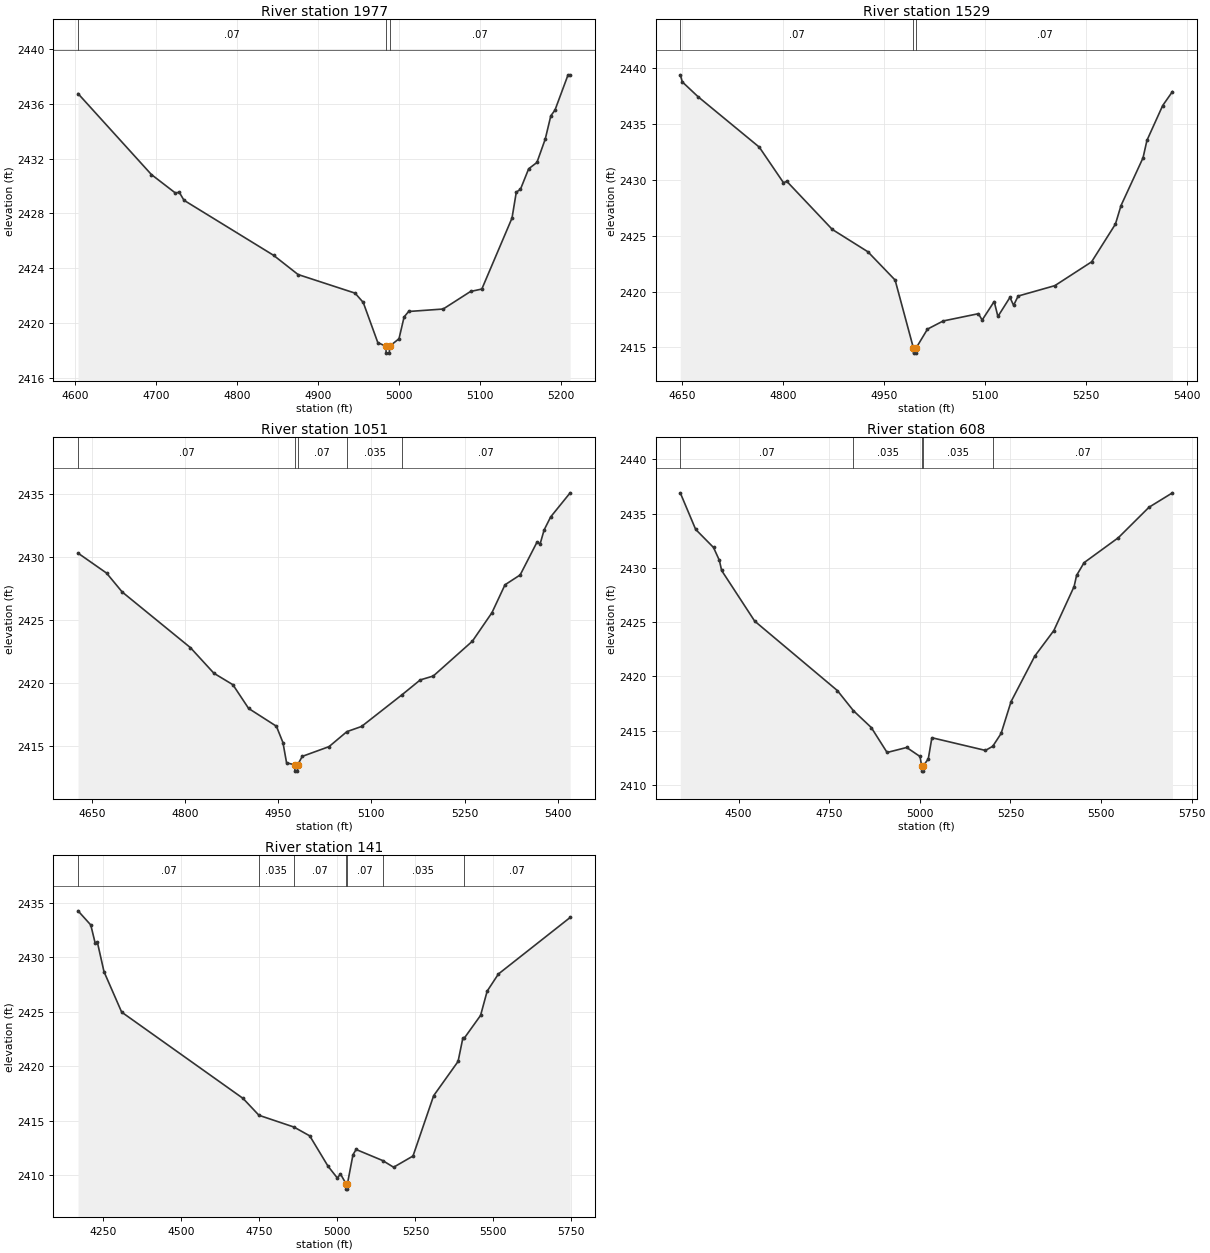
Type RM Length L Ch R = 1,1977,448,448,448
BEGIN DESCRIPTION:
elmc138
END DESCRIPTION:
XS GIS Cut Line= 3
      1459055.00      6786888.02      1459102.82      6786494.12
      1459055.00      6786287.99
#Sta/Elev= 30
  4603.2 2436.75  4693.9 2430.84  4723.4 2429.50  4728.4 2429.54  4734.2 2428.96
  4845.0 2424.94  4875.2 2423.54  4945.7 2422.18  4955.8 2421.50  4973.8 2418.57
  4983.8 2418.30  4984.1 2417.80  4988.0 2417.80  4988.3 2418.30  5000.0 2418.85
  5006.3 2420.44  5011.9 2420.84  5054.6 2421.02  5088.4 2422.30  5102.4 2422.48
  5139.7 2427.66  5145.0 2429.55  5150.2 2429.77  5160.3 2431.26  5170.5 2431.72
  5180.8 2433.43  5187.7 2435.13  5192.8 2435.54  5209.0 2438.12  5211.6 2438.12
#Mann=3,-1,0
  4603.2    0.07       0  4983.8    0.07       0  4988.3    0.07       0
Bank Sta=4983.8,4988.3
Exp/Cntr=0.3,0.1

Type RM Length L Ch R = 1,1529,478,478,478
BEGIN DESCRIPTION:
elmc137
END DESCRIPTION:
XS GIS Cut Line= 3
      1459409.38      6786934.20      1459456.62      6786584.88
      1459304.99      6786237.97
#Sta/Elev= 30
  4647.5 2439.40  4650.4 2438.77  4673.9 2437.44  4764.8 2432.93  4800.7 2429.75
  4805.8 2429.86  4873.3 2425.56  4926.2 2423.56  4966.6 2421.03  4993.6 2414.99
  4994.0 2414.49  4997.9 2414.49  4998.2 2414.99  5014.7 2416.64  5038.1 2417.37
  5090.4 2418.02  5095.9 2417.45  5113.8 2419.11  5119.3 2417.77  5137.2 2419.48
  5142.6 2418.77  5149.4 2419.60  5203.9 2420.53  5258.5 2422.66  5293.9 2426.04
  5302.2 2427.70  5334.9 2431.97  5340.7 2433.53  5364.1 2436.65  5378.6 2437.90
#Mann=3,-1,0
  4647.5    0.07       0  4993.6    0.07       0  4998.2    0.07       0
Bank Sta=4993.6,4998.2
Exp/Cntr=0.3,0.1

Type RM Length L Ch R = 1,1051,443,443,443
BEGIN DESCRIPTION:
elmc136
END DESCRIPTION:
XS GIS Cut Line= 3
      1459755.00      6786788.01      1459882.34      6786438.17
      1459755.01      6786038.04
#Sta/Elev= 30
  4627.7 2430.31  4673.6 2428.73  4698.8 2427.23  4808.6 2422.82  4846.4 2420.79
  4877.0 2419.88  4902.3 2418.00  4947.0 2416.59  4957.6 2415.29  4963.4 2413.69
  4976.5 2413.53  4976.9 2413.03  4980.9 2413.03  4981.2 2413.53  4988.7 2414.20
  5031.7 2414.97  5060.5 2416.16  5084.1 2416.57  5149.4 2419.09  5178.6 2420.26
  5199.6 2420.57  5262.5 2423.33  5294.0 2425.59  5315.0 2427.80  5339.4 2428.58
  5366.4 2431.17  5371.6 2431.05  5378.0 2432.15  5388.5 2433.18  5419.9 2435.09
#Mann=5,-1,0
  4627.7    0.07       0  4976.5    0.07       0  4981.2    0.07       0
  5060.5   0.035       0  5149.4    0.07       0
Bank Sta=4976.5,4981.2
Exp/Cntr=0.3,0.1

Type RM Length L Ch R = 1,608,467,467,467
BEGIN DESCRIPTION:
elmc135
END DESCRIPTION:
XS GIS Cut Line= 3
      1459948.55      6786977.96      1460283.74      6786365.88
      1460089.72      6785735.30
#Sta/Elev= 30
  4339.4 2436.91  4381.7 2433.55  4431.0 2431.88  4447.1 2430.70  4453.4 2429.76
  4544.6 2425.09  4772.6 2418.69  4817.0 2416.83  4866.2 2415.28  4909.8 2412.98
  4963.9 2413.44  5000.6 2412.61  5005.1 2411.76  5005.5 2411.26  5009.5 2411.26
  5009.8 2411.76  5023.4 2412.38  5033.4 2414.34  5181.1 2413.17  5201.3 2413.55
  5224.3 2414.73  5251.8 2417.67  5317.1 2421.86  5369.8 2424.22  5425.7 2428.28
  5432.6 2429.31  5453.2 2430.48  5547.7 2432.78  5632.3 2435.59  5697.0 2436.92
#Mann=5,-1,0
  4339.4    0.07       0  4817.0   0.035       0  5005.1   0.035       0
  5009.8   0.035       0  5201.3    0.07       0
Bank Sta=5005.1,5009.8
Exp/Cntr=0.3,0.1

Type RM Length L Ch R = 1,141,0,0,0
BEGIN DESCRIPTION:
elmc221
END DESCRIPTION:
XS GIS Cut Line= 4
      1460050.56      6787031.38      1460492.61      6786603.90
      1460516.90      6786195.86      1460210.88      6785734.41
#Sta/Elev= 30
  4168.6 2434.28  4209.5 2432.98  4223.6 2431.31  4230.6 2431.40  4251.9 2428.69
  4308.5 2424.98  4697.5 2417.06  4748.5 2415.51  4860.6 2414.43  4911.3 2413.62
  4969.8 2410.84  4999.8 2409.75  5009.8 2410.12  5027.5 2409.23  5027.8 2408.73
  5031.9 2408.73  5032.2 2409.23  5049.9 2411.89  5059.9 2412.37  5145.3 2411.35
  5180.1 2410.74  5242.3 2411.77  5308.5 2417.31  5386.7 2420.45  5401.8 2422.56
  5406.1 2422.57  5458.9 2424.68  5480.0 2426.91  5516.0 2428.48  5746.0 2433.67
#Mann=7,-1,0
  4168.6    0.07       0  4748.5   0.035       0  4860.6    0.07       0
  5027.5    0.07       0  5032.2    0.07       0  5145.3   0.035       0
  5406.1    0.07       0
Bank Sta=5027.5,5032.2
Exp/Cntr=0.3,0.1

Chan Stop Cuts=-1