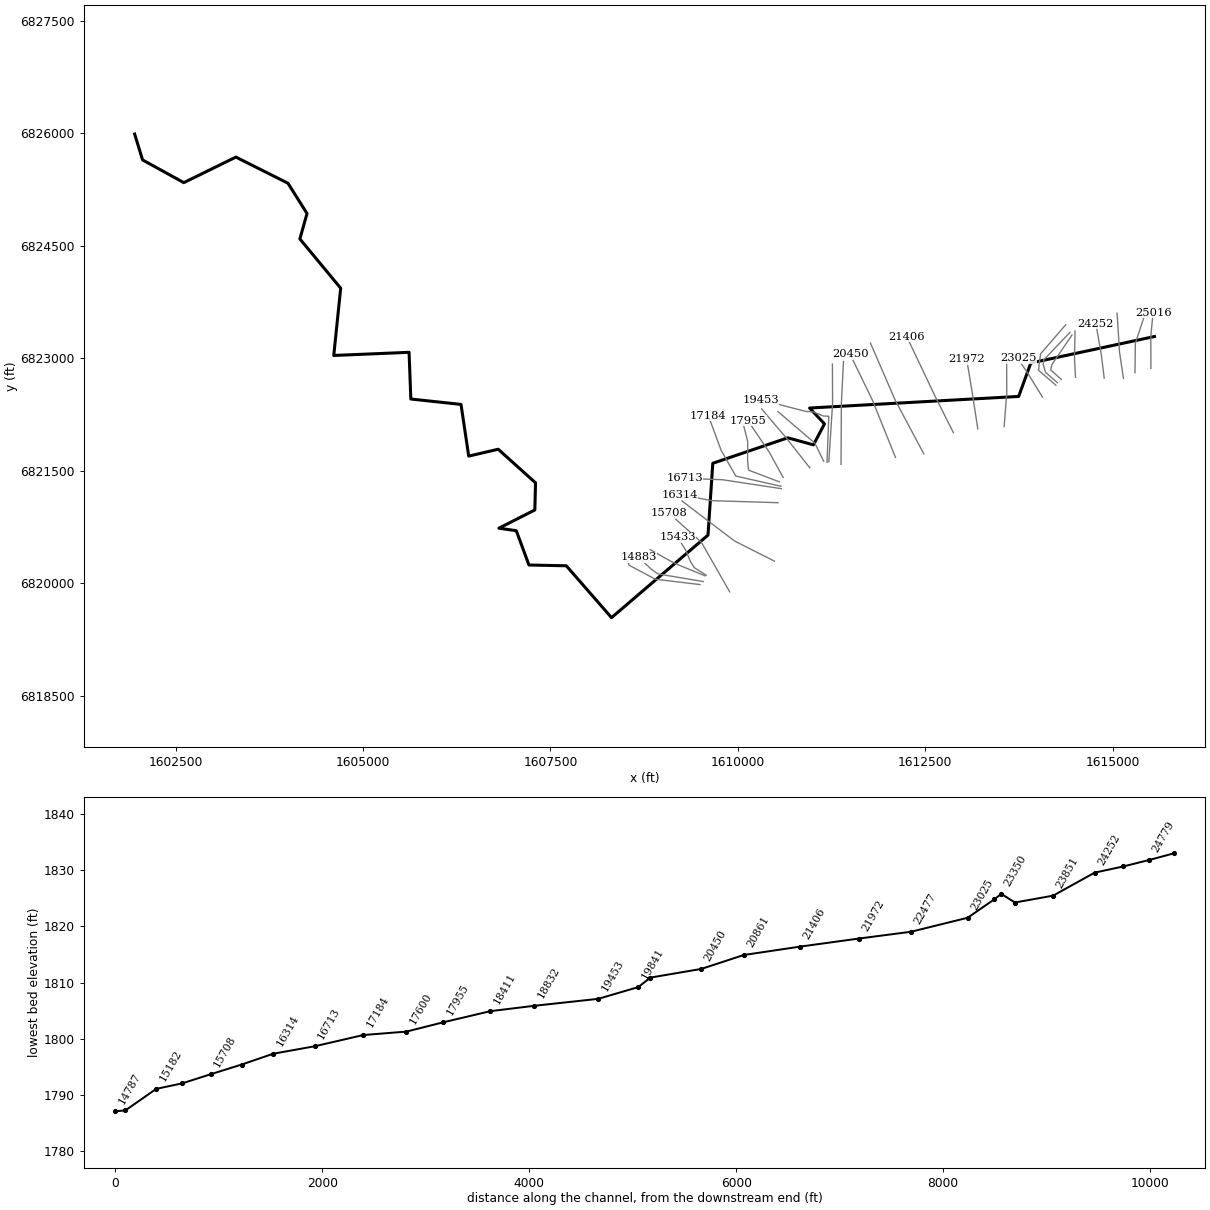
--- Elm 02 01.prj (project) ---

Proj Title=Elm 02 01 Base Level Engineering
Current Plan=p01
Default Exp/Contr=0.3,0.1
English Units
Geom File=g01
Flow File=f01
Plan File=p01
Y Axis Title=Elevation
X Axis Title(PF)=Main Channel Distance
X Axis Title(XS)=Station
BEGIN DESCRIPTION:
Elm 02 01
END DESCRIPTION:
DSS Export Rating Curves= 0
DSS Export Rating Curve Sorted= 0
DSS Export Volume Flow Curves= 0
DXF OffsetX= 0
DXF OffsetY= 0
DXF ScaleX= 1
DXF ScaleY= 10

--- Elm 02 01.p01 (plan) ---

Plan Title=Multiple Run
Short Identifier=Multiple
Geom File=g01
Flow File=f01
Subcritical Flow
K Sum by GR= 0
Std Step Tol= 0.01
Critical Tol= 0.01
Num of Std Step Trials= 20
Max Error Tol= 0.3
Flow Tol Ratio= 0.001
Split Flow NTrial= 30
Split Flow Tol= 0.02
Split Flow Ratio= 0.02
Log Output Level= 0
Friction Slope Method= 1
Unsteady Friction Slope Method= 2
Unsteady Bridges Friction Slope Method= 1
Parabolic Critical Depth
Global Vel Dist=  1 , 1 , 1
Global Log Level= 0
CheckData=True
Encroach Param= -1, 0, 0, 0
BEGIN DESCRIPTION:
Multiple Run
END DESCRIPTION:

--- Elm 02 01.f01 (steady flow) ---

Flow Title=Multiple
Number of Profiles=7
Profile Names=10-year,25-year,50-year,1pct_min,100-year,1pct_plu,500-year
River Rch & RM= Elm 02 01,Reach-1,25016
     201     275     334     252     404     556     600
River Rch & RM= Elm 02 01,Reach-1,18832
     205     280     340     256     410     564     605
River Rch & RM= Elm 02 01,Reach-1,15433
     348     490     608     467     748    1030    1150
River Rch & RM= Elm 02 01,Reach-1,14452
     514     736     925     719    1150    1580    1810
River Rch & RM= Elm 02 01,Reach-1,3549
     576     828    1040     813    1300    1790    2060
Boundary for River Rch & Prof#=Elm 02 01,Reach-1,1
Up Type=0
Dn Type=3
Dn Slope=0.001
Boundary for River Rch & Prof#=Elm 02 01,Reach-1,2
Up Type=0
Dn Type=3
Dn Slope=0.001
Boundary for River Rch & Prof#=Elm 02 01,Reach-1,3
Up Type=0
Dn Type=3
Dn Slope=0.001
Boundary for River Rch & Prof#=Elm 02 01,Reach-1,4
Up Type=0
Dn Type=3
Dn Slope=0.001
Boundary for River Rch & Prof#=Elm 02 01,Reach-1,5
Up Type=0
Dn Type=3
Dn Slope=0.001
Boundary for River Rch & Prof#=Elm 02 01,Reach-1,6
Up Type=0
Dn Type=3
Dn Slope=0.001
Boundary for River Rch & Prof#=Elm 02 01,Reach-1,7
Up Type=0
Dn Type=3
Dn Slope=0.001

--- Elm 02 01.g01 (geometry) ---

Geom Title=Existing Conditions
Program Version=4.10

River Reach=Elm 02 01       ,Reach-1
Reach XY= 30
        1615555.        6823288.      1613906.25      6822934.64
      1613744.53      6822488.93      1610956.01      6822334.39
      1611154.82      6822122.92      1611007.31      6821843.08
      1610665.15      6821937.07      1609665.11      6821597.43
      1609601.38       6820639.5       1608314.8      6819538.71
      1607711.48      6820230.31      1607213.48      6820240.63
      1607044.66      6820698.24      1606812.36      6820731.57
      1607291.88      6820974.78      1607301.47      6821336.53
      1606803.53      6821784.54      1606409.99        6821693.
      1606307.45      6822382.53       1605638.2      6822454.42
      1605614.71      6823077.25       1604610.4      6823035.29
      1604702.62      6823932.47      1604158.33       6824589.7
      1604253.79      6824928.41      1603999.38      6825332.38
      1603305.02      6825680.92      1602610.85      6825340.06
      1602060.41      6825643.17        1601955.        6825988.

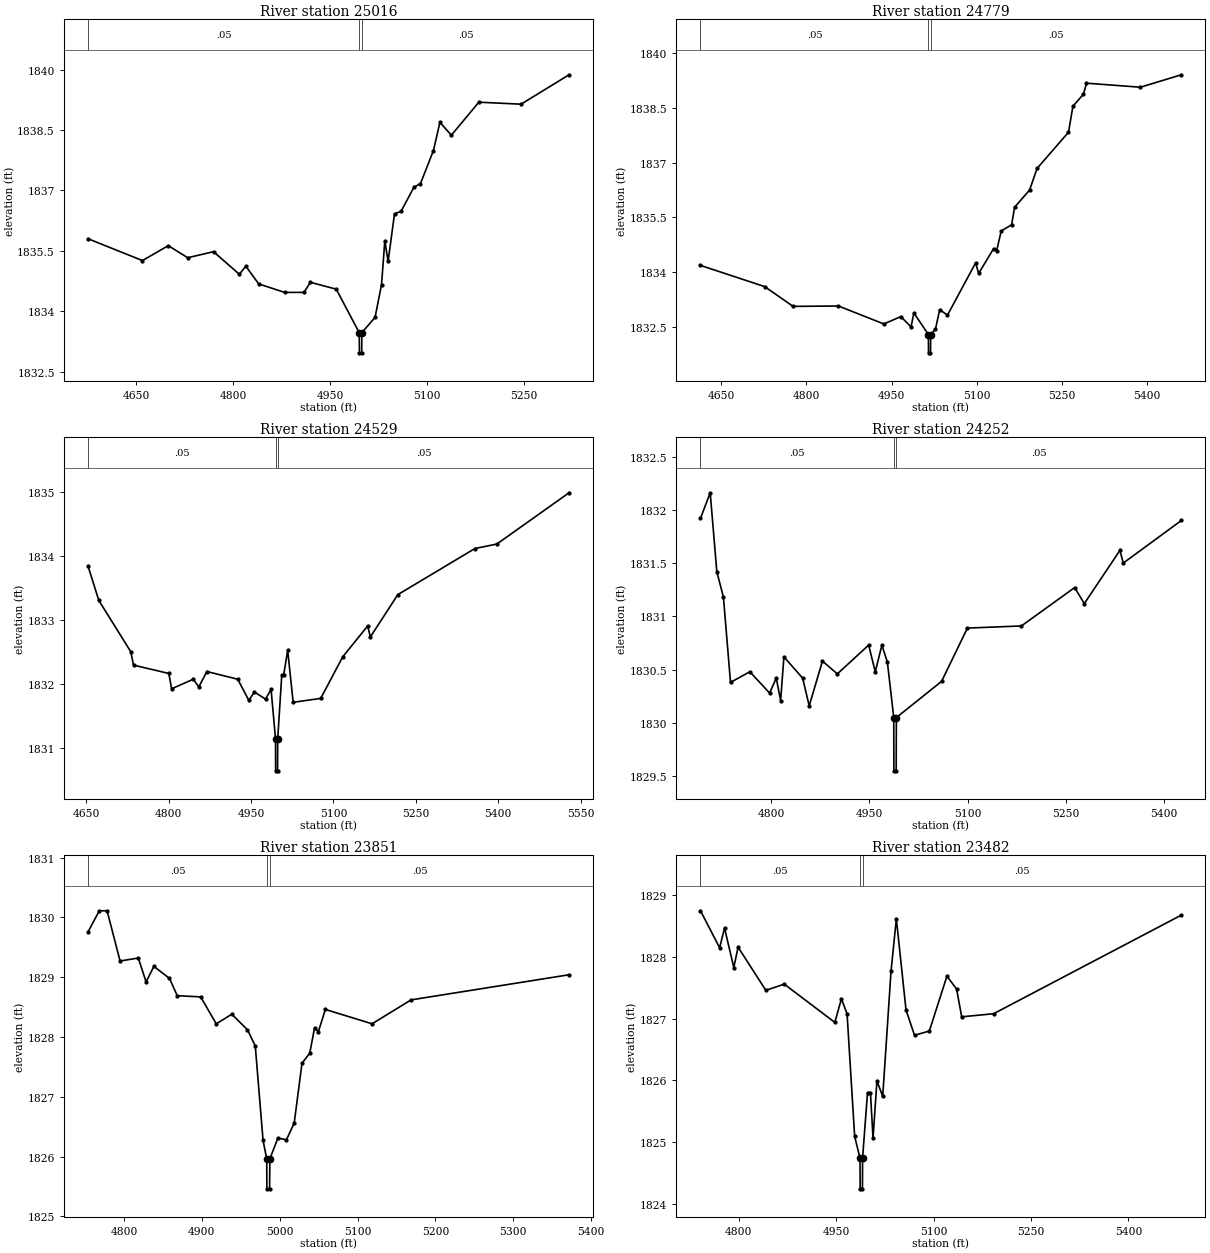
Type RM Length L Ch R = 1 ,25016   ,237,237,237
BEGIN DESCRIPTION:
Elm 02 01 24901.344
END DESCRIPTION:
XS GIS Cut Line= 3
      1615507.96      6822863.91      1615506.67      6823288.31
      1615537.04      6823606.97
#Sta/Elev= 30
  4575.6  1835.8  4659.7 1835.26  4699.7 1835.63  4729.7 1835.33  4769.7 1835.48
  4809.7 1834.92  4819.7 1835.12  4839.7 1834.68  4879.7 1834.47  4909.7 1834.47
  4919.7 1834.72  4959.7 1834.55  4995.3 1833.47  4995.6 1832.97  4999.1 1832.97
  4999.3 1833.47  5019.8 1833.85  5029.8 1834.66  5034.9 1835.75    5040 1835.24
  5049.9 1836.42    5060 1836.48    5080 1837.08  5090.1 1837.17  5110.2 1837.99
  5120.2 1838.69  5137.9 1838.37  5180.5 1839.19  5245.8 1839.14  5320.1 1839.87
#Mann= 3 ,-1 , 0
  4575.6     .05       0  4995.3     .03       0  4999.3     .05       0
Bank Sta=4995.3,4999.3
XS Rating Curve= 0 ,0
Exp/Cntr=0.3,0.1

Type RM Length L Ch R = 1 ,24779   ,250,250,250
BEGIN DESCRIPTION:
Elm 02 01 24778.92
END DESCRIPTION:
XS GIS Cut Line= 3
      1615295.87      6822804.79      1615300.21      6823197.55
      1615443.44      6823629.44
#Sta/Elev= 30
  4613.2 1834.19  4726.4 1833.61  4776.4 1833.07  4856.4 1833.08  4936.4 1832.59
  4966.4 1832.79  4984.4 1832.51  4989.4 1832.89    5015  1832.3  5015.2  1831.8
  5018.7  1831.8    5019  1832.3  5027.5 1832.45  5034.9 1832.98  5048.6 1832.83
  5098.3 1834.26  5103.6 1833.97    5130 1834.65  5135.3 1834.59  5143.4 1835.13
  5161.7  1835.3    5167 1835.78  5193.4 1836.25  5206.6 1836.84    5262 1837.83
  5269.8 1838.54  5288.4 1838.87  5293.7 1839.17  5388.8 1839.06    5461  1839.4
#Mann= 3 ,-1 , 0
  4613.2     .05       0    5015     .05       0    5019     .05       0
Bank Sta=5015,5019
XS Rating Curve= 0 ,0
Exp/Cntr=0.3,0.1

Type RM Length L Ch R = 1 ,24529   ,277,277,277
BEGIN DESCRIPTION:
Elm 02 01 24528.54
END DESCRIPTION:
XS GIS Cut Line= 3
      1615141.79      6822728.78       1615089.7      6823078.19
      1615057.15        6823599.
#Sta/Elev= 30
  4653.7 1833.84  4673.1 1833.31  4731.2 1832.51  4736.3  1832.3  4800.5 1832.17
  4805.6 1831.93    4845 1832.08  4855.1 1831.96  4869.8  1832.2  4925.9 1832.08
  4946.1 1831.75  4956.2 1831.88  4976.5 1831.77  4986.6 1831.92  4994.7 1831.15
  4994.9 1830.65  4998.4 1830.65  4998.7 1831.15    5006 1832.14  5009.4 1832.14
  5016.8 1832.53  5026.8 1831.72  5076.9 1831.78    5117 1832.43  5162.3 1832.91
  5167.3 1832.74  5217.2  1833.4  5357.5 1834.12  5397.5 1834.19  5528.8 1834.99
#Mann= 3 ,-1 , 0
  4653.7     .05       0  4994.7     .05       0  4998.7     .05       0
Bank Sta=4994.7,4998.7
XS Rating Curve= 0 ,0
Exp/Cntr=0.3,0.1

Type RM Length L Ch R = 1 ,24252   ,401,401,401
BEGIN DESCRIPTION:
Elm 02 01 24252.45
END DESCRIPTION:
XS GIS Cut Line= 3
      1614885.05       6822733.3       1614847.3      6823041.84
      1614774.39      6823458.47
#Sta/Elev= 30
  4692.5 1831.92  4707.3 1832.16  4717.4 1831.42  4727.5 1831.18  4738.3 1830.38
  4767.8 1830.48    4798 1830.28  4808.1 1830.42  4814.8 1830.21  4819.8 1830.62
  4848.4 1830.42  4858.4 1830.16  4878.6 1830.58  4901.3 1830.46  4949.1 1830.73
  4959.2 1830.48  4969.3 1830.73  4977.7 1830.57  4987.4 1830.05  4987.6 1829.55
  4991.1 1829.55  4991.4 1830.05  5060.4 1830.39  5099.8 1830.89  5182.2 1830.91
  5263.4 1831.27  5278.2 1831.12  5332.6 1831.62  5337.6  1831.5  5426.3  1831.9
#Mann= 3 ,-1 , 0
  4692.5     .05       0  4987.4     .05       0  4991.4     .05       0
Bank Sta=4987.4,4991.4
XS Rating Curve= 0 ,0
Exp/Cntr=0.3,0.1

Type RM Length L Ch R = 1 ,23851   ,369,369,369
BEGIN DESCRIPTION:
Elm 02 01 23851.18
END DESCRIPTION:
XS GIS Cut Line= 3
      1614502.24      6822743.72      1614489.23      6822991.06
      1614495.74      6823360.82
#Sta/Elev= 30
  4754.1 1829.76  4768.4 1830.11  4778.4 1830.11  4795.1 1829.27  4818.5 1829.32
  4828.5 1828.92  4838.5 1829.18  4858.5 1828.98  4868.5 1828.69  4898.6 1828.67
  4918.6 1828.22  4938.6 1828.38  4958.7 1828.12  4968.7 1827.85  4978.7 1826.27
  4983.4 1825.96  4983.6 1825.46  4987.1 1825.46  4987.4 1825.96  4997.8 1826.31
  5008.7 1826.28  5018.7 1826.56  5028.7 1827.56  5038.7 1827.73  5044.8 1828.15
  5049.8 1828.09  5058.7 1828.46  5118.7 1828.22  5168.8 1828.62  5371.6 1829.04
#Mann= 3 ,-1 , 0
  4754.1     .05       0  4983.4     .05       0  4987.4     .05       0
Bank Sta=4983.4,4987.4
XS Rating Curve= 0 ,0
Exp/Cntr=0.3,0.1

Type RM Length L Ch R = 1 ,23482   ,132,132,132
BEGIN DESCRIPTION:
Elm 02 01 23481.93
END DESCRIPTION:
XS GIS Cut Line= 4
      1614314.39      6822715.48      1614172.28      6822841.32
      1614186.38      6822911.85      1614455.52       6823307.8
#Sta/Elev= 30
  4741.1 1828.75  4770.6 1828.15  4778.1 1828.47  4792.4 1827.83    4799 1828.16
  4841.7 1827.46  4870.1 1827.56  4947.9 1826.94  4958.1 1827.32  4966.8 1827.08
  4978.5 1825.09  4986.7 1824.74    4987 1824.24  4990.5 1824.24  4990.7 1824.74
  4998.3  1825.8  5002.8  1825.8  5006.8 1825.06  5012.8 1825.99  5021.7 1825.74
  5034.5 1827.77  5042.7 1828.62  5057.6 1827.14  5070.7 1826.73  5093.5  1826.8
  5120.6 1827.69  5135.5 1827.48  5143.3 1827.03  5192.4 1827.08  5481.6 1828.68
#Mann= 3 ,-1 , 0
  4741.1     .05       0  4986.7     .05       0  4990.7     .05       0
Bank Sta=4986.7,4990.7
XS Rating Curve= 0 ,0
Exp/Cntr=0.3,0.1

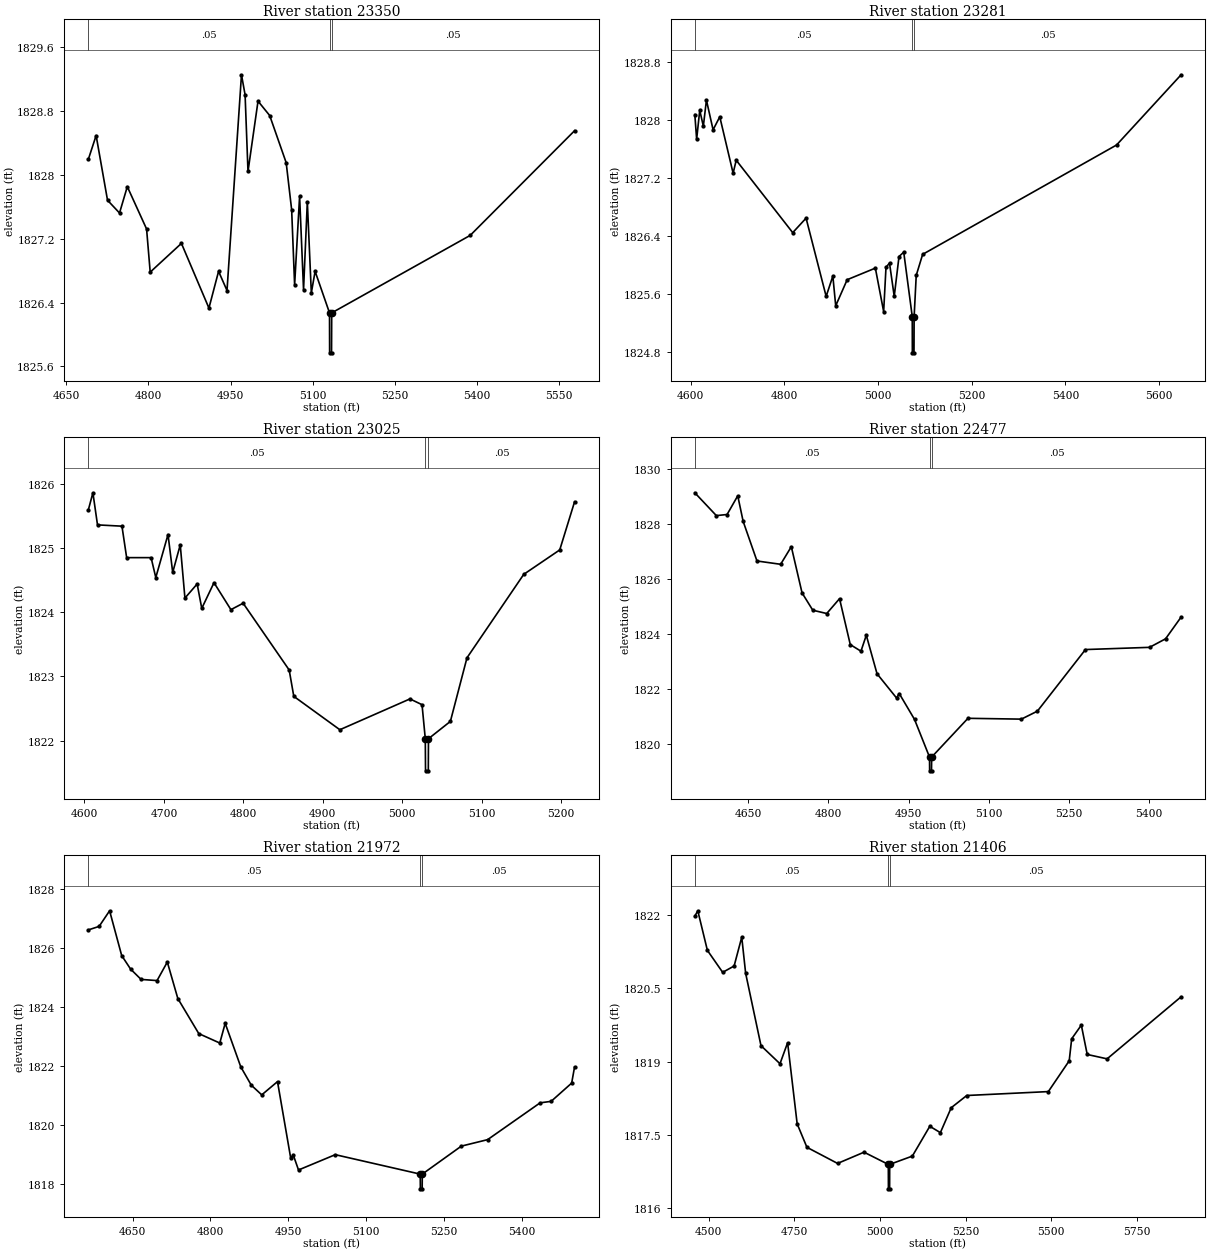
Type RM Length L Ch R = 1 ,23350   ,69,69,69
BEGIN DESCRIPTION:
Elm 02 01 23350.49
END DESCRIPTION:
XS GIS Cut Line= 5
      1614260.17      6822673.13      1614102.83      6822809.86
      1614072.45      6822910.77      1614076.79       6822973.7
      1614428.87      6823343.62
#Sta/Elev= 30
  4690.3 1828.19  4704.6 1828.49  4725.4 1827.68  4747.3 1827.52  4761.5 1827.85
  4796.7 1827.32  4803.3 1826.78  4860.3 1827.14  4910.5 1826.33  4928.1 1826.79
  4943.5 1826.55  4969.9 1829.25  4976.5    1829  4981.8 1828.04  5000.1 1828.92
  5021.4 1828.74  5051.5 1828.15  5061.5 1827.56  5066.9 1826.62    5076 1827.73
  5083.2 1826.56  5090.1 1827.66  5097.4 1826.52  5104.3 1826.79  5130.6 1826.27
  5130.8 1825.77  5134.3 1825.77  5134.6 1826.27  5387.4 1827.24  5577.9 1828.55
#Mann= 3 ,-1 , 0
  4690.3     .05       0  5130.6     .05       0  5134.6     .05       0
Bank Sta=5130.6,5134.6
XS Rating Curve= 0 ,0
Exp/Cntr=0.3,0.1

Type RM Length L Ch R = 1 ,23281   ,256,256,256
BEGIN DESCRIPTION:
Elm 02 01 23281.36
END DESCRIPTION:
XS GIS Cut Line= 6
      1614240.63      6822638.42      1614073.54      6822782.73
       1614010.6       6822835.9       1614018.2      6822925.96
      1614037.73      6823058.34       1614372.2      6823444.97
#Sta/Elev= 30
  4608.5 1828.08  4612.4 1827.74    4619 1828.14  4626.7 1827.92  4633.3 1828.28
  4647.5 1827.87  4661.8 1828.05  4690.3 1827.27  4696.9 1827.45  4817.6 1826.45
  4846.1 1826.65    4889 1825.57  4903.3 1825.85  4909.4 1825.44  4933.9  1825.8
  4994.1 1825.96  5011.8 1825.36  5016.8 1825.97  5024.3 1826.03  5034.4 1825.57
  5044.6 1826.12  5054.7 1826.18  5072.9 1825.29  5073.1 1824.79  5076.6 1824.79
  5076.9 1825.29  5081.4 1825.86  5095.1 1826.15  5509.2 1827.66  5647.1 1828.63
#Mann= 3 ,-1 , 0
  4608.5     .05       0  5072.9     .05       0  5076.9     .05       0
Bank Sta=5072.9,5076.9
XS Rating Curve= 0 ,0
Exp/Cntr=0.3,0.1

Type RM Length L Ch R = 1 ,23025   ,548,548,548
BEGIN DESCRIPTION:
Elm 02 01 23025.15
END DESCRIPTION:
XS GIS Cut Line= 4
      1614063.21      6822478.41      1613850.54      6822823.46
       1613764.9       6822945.2      1613741.99      6822998.74
#Sta/Elev= 30
  4604.8 1825.59  4610.6 1825.86  4616.4 1825.36  4647.2 1825.34  4653.1 1824.85
  4683.9 1824.85  4689.8 1824.54  4705.2 1825.21  4711.1 1824.62  4720.6 1825.05
  4726.5 1824.22  4741.9 1824.44  4747.7 1824.06  4763.1 1824.46  4784.4 1824.04
  4799.8 1824.14  4857.8  1823.1  4863.6 1822.69  4921.6 1822.17  5009.9 1822.65
  5025.1 1822.56  5029.2 1822.03  5029.5 1821.53    5033 1821.53  5033.2 1822.03
  5060.8  1822.3  5081.7 1823.29  5153.2 1824.59  5198.5 1824.97  5217.2 1825.72
#Mann= 3 ,-1 , 0
  4604.8     .05       0  5029.2     .05       0  5033.2     .05       0
Bank Sta=5029.2,5033.2
XS Rating Curve= 0 ,0
Exp/Cntr=0.3,0.1

Type RM Length L Ch R = 1 ,22477   ,505,505,505
BEGIN DESCRIPTION:
Elm 02 01 22476.69
END DESCRIPTION:
XS GIS Cut Line= 3
      1613551.06      6822087.79      1613585.78      6822541.34
      1613583.99      6822997.06
#Sta/Elev= 30
  4549.7 1829.15    4590 1828.32  4610.1 1828.36  4630.1 1829.04  4640.2 1828.11
  4666.1 1826.67  4710.4 1826.55  4730.4 1827.19  4750.5 1825.51  4770.6 1824.88
  4796.7 1824.76  4820.7  1825.3  4840.8 1823.63  4860.8 1823.39  4870.8 1823.97
  4890.9 1822.57  4927.4 1821.69  4932.5 1821.85  4961.1 1820.91  4989.2 1819.54
  4989.4 1819.04  4992.9 1819.04  4993.2 1819.54  5061.2 1820.95  5161.2 1820.92
  5191.2 1821.21  5281.2 1823.45  5401.2 1823.53  5431.2 1823.84  5460.3 1824.63
#Mann= 3 ,-1 , 0
  4549.7     .05       0  4989.2     .05       0  4993.2     .05       0
Bank Sta=4989.2,4993.2
XS Rating Curve= 0 ,0
Exp/Cntr=0.3,0.1

Type RM Length L Ch R = 1 ,21972   ,566,566,566
BEGIN DESCRIPTION:
Elm 02 01 21972.13
END DESCRIPTION:
XS GIS Cut Line= 3
       1613199.5      6822057.36      1613132.22      6822493.59
      1613052.02      6822983.48
#Sta/Elev= 30
  4564.4 1826.62  4585.3 1826.74  4605.5 1827.27  4628.8 1825.75    4646 1825.29
  4666.2 1824.94    4697  1824.9  4716.8 1825.53  4737.1 1824.29  4777.5  1823.1
    4818 1822.78  4828.4 1823.45  4858.5 1821.97  4878.7 1821.35  4898.9 1821.02
  4929.3 1821.47  4954.7 1818.88  4959.7 1818.98  4969.8 1818.47  5040.7 1818.99
  5204.5 1818.33  5204.8 1817.83  5208.3 1817.83  5208.5 1818.33  5283.8 1819.28
  5334.5  1819.5  5435.8 1820.75    5457  1820.8  5496.6 1821.42  5502.2 1821.97
#Mann= 3 ,-1 , 0
  4564.4     .05       0  5204.5     .05       0  5208.5     .05       0
Bank Sta=5204.5,5208.5
XS Rating Curve= 0 ,0
Exp/Cntr=0.3,0.1

Type RM Length L Ch R = 1 ,21406   ,545,545,545
BEGIN DESCRIPTION:
Elm 02 01 21406.34
END DESCRIPTION:
XS GIS Cut Line= 3
      1612873.98       6822005.3      1612628.75      6822493.59
      1612253.45      6823283.23
#Sta/Elev= 30
    4459 1821.98  4467.7 1822.09  4495.7 1821.28  4540.4 1820.83  4573.8 1820.96
  4596.1 1821.55  4607.5 1820.81  4652.3 1819.33  4707.8 1818.96  4730.1 1819.39
    4758 1817.73  4786.5 1817.25  4876.1 1816.92  4953.4 1817.15  5024.3  1816.9
  5024.6  1816.4  5028.1  1816.4  5028.3  1816.9  5094.5 1817.07  5145.5 1817.68
  5176.4 1817.55  5208.1 1818.06  5253.5 1818.31  5491.8 1818.39  5552.8 1819.02
    5560 1819.47  5588.2 1819.75  5605.4 1819.15  5663.5 1819.06  5879.7 1820.33
#Mann= 3 ,-1 , 0
    4459     .05       0  5024.3    .035       0  5028.3     .05       0
Bank Sta=5024.3,5028.3
XS Rating Curve= 0 ,0
Exp/Cntr=0.3,0.1

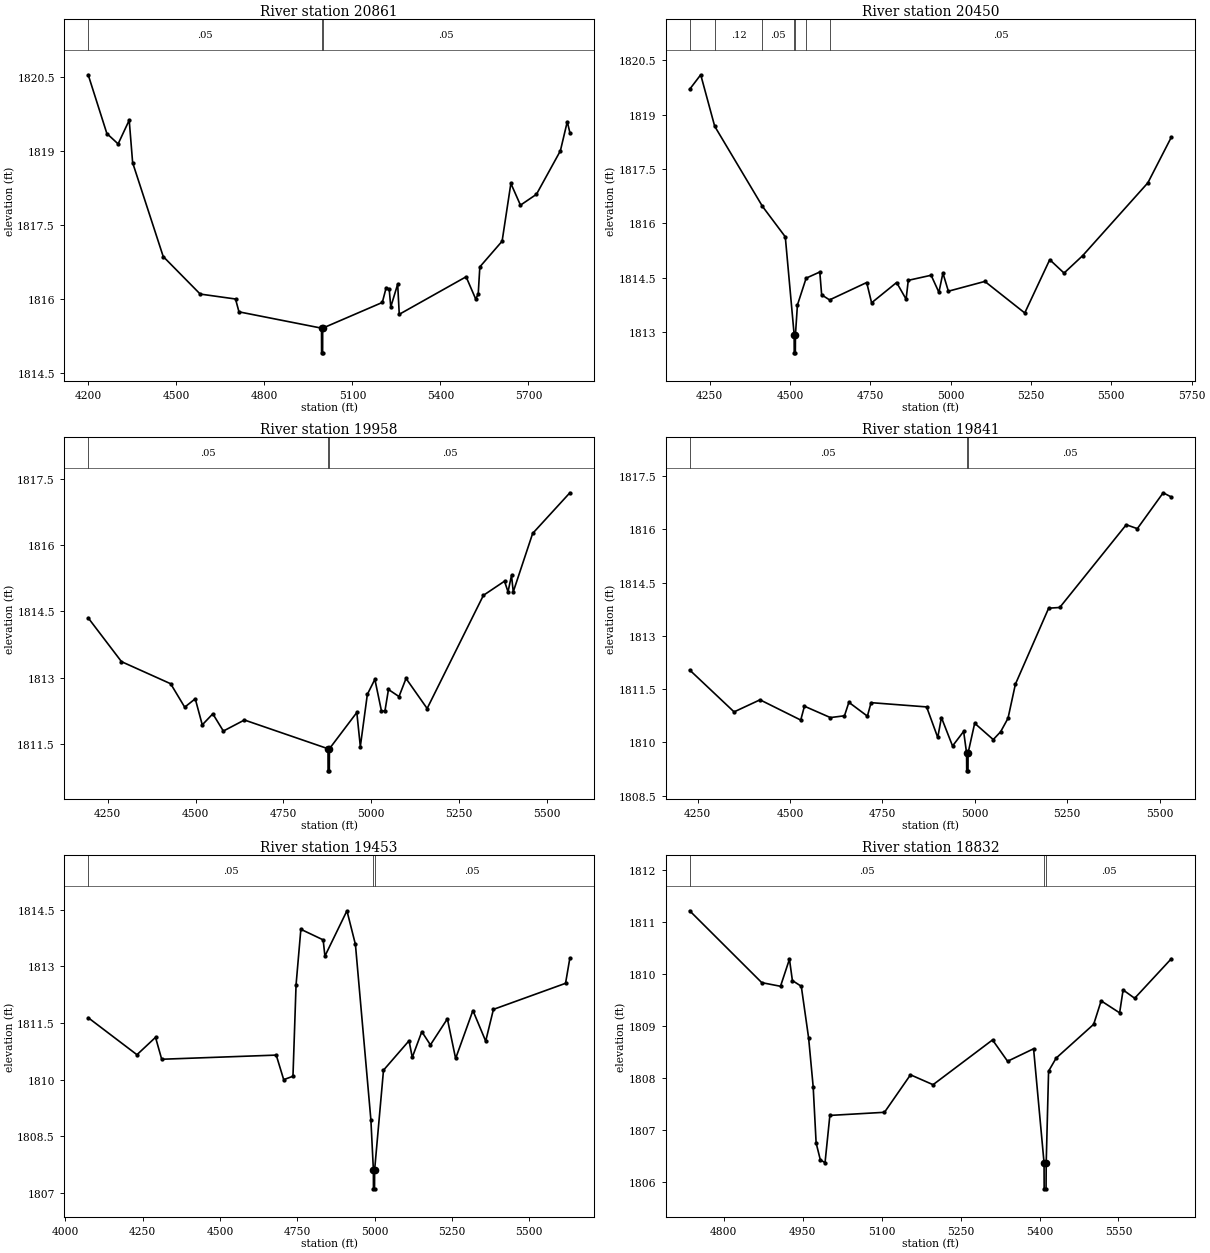
Type RM Length L Ch R = 1 ,20861   ,411,411,411
BEGIN DESCRIPTION:
Elm 02 01 20860.53
END DESCRIPTION:
XS GIS Cut Line= 3
      1612478.84      6821724.62      1612099.05      6822436.45
      1611767.03      6823202.49
#Sta/Elev= 30
  4199.5 1820.54  4263.2 1819.35  4301.5 1819.14  4339.3 1819.62    4351 1818.76
  4455.2 1816.86  4581.2  1816.1  4701.6    1816  4713.4 1815.74  4994.7 1815.41
    4995 1814.91  4998.5 1814.91  4998.7 1815.41  5201.9 1815.93  5215.1 1816.23
  5225.4  1816.2  5230.8 1815.84  5254.3  1816.3  5259.7 1815.69  5487.5 1816.45
  5520.2    1816  5528.8  1816.1  5534.3 1816.65  5610.2 1817.17  5640.1 1818.34
  5672.8  1817.9  5727.3 1818.12  5808.8    1819  5832.3 1819.59  5841.2 1819.37
#Mann= 3 ,-1 , 0
  4199.5     .05       0  4994.7     .05       0  4998.7     .05       0
Bank Sta=4994.7,4998.7
XS Rating Curve= 0 ,0
Exp/Cntr=0.3,0.1

Type RM Length L Ch R = 1 ,20450   ,492,492,492
BEGIN DESCRIPTION:
Elm 02 01 20450.09
END DESCRIPTION:
XS GIS Cut Line= 3
      1612101.21      6821676.93      1611795.23      6822436.45
      1611497.93      6823048.42
#Sta/Elev= 30
  4187.6  1819.7    4222  1820.1  4265.5 1818.68  4414.2 1816.47  4485.2 1815.63
  4512.8 1812.93    4513 1812.43  4516.5 1812.43  4516.8 1812.93    4523 1813.75
  4550.1 1814.49  4592.6 1814.66  4598.4 1814.03    4623 1813.89  4738.6 1814.37
  4753.8 1813.81  4831.7 1814.37  4861.2 1813.91    4868 1814.43  4939.1 1814.57
  4963.3  1814.1  4975.8 1814.63  4992.8 1814.13  5106.3  1814.4  5230.5 1813.53
  5308.3    1815  5352.8 1814.63  5410.7 1815.11  5613.7 1817.12  5686.8 1818.38
#Mann= 7 ,-1 , 0
  4187.6     .05       0  4265.5     .12       0  4414.2     .05       0
  4512.8     .03       0  4516.8     .05       0  4550.1     .12       0
    4623     .05       0
Bank Sta=4512.8,4516.8
XS Rating Curve= 0 ,0
Exp/Cntr=0.3,0.1

Type RM Length L Ch R = 1 ,19958   ,117,117,117
BEGIN DESCRIPTION:
Elm 02 01 19957.98
END DESCRIPTION:
XS GIS Cut Line= 3
      1611375.61      6821583.21      1611379.95      6822394.89
      1611408.12      6822953.89
#Sta/Elev= 30
  4194.2 1814.35    4289 1813.36    4429 1812.86    4469 1812.33    4499 1812.52
    4519 1811.93    4549 1812.18    4579 1811.79    4639 1812.04    4877 1811.39
  4877.2 1810.89  4880.7 1810.89    4881 1811.39    4959 1812.21    4969 1811.44
    4989 1812.62  5010.4 1812.96    5029 1812.25    5039 1812.24  5049.1 1812.73
  5079.1 1812.57  5099.1 1812.98  5159.2  1812.3  5319.4 1814.86  5379.5 1815.18
  5389.5 1814.94  5399.4 1815.31  5404.4 1814.94  5459.6 1816.26  5565.6 1817.18
#Mann= 3 ,-1 , 0
  4194.2     .05       0    4877     .03       0    4881     .05       0
Bank Sta=4877,4881
XS Rating Curve= 0 ,0
Exp/Cntr=0.3,0.1

Type RM Length L Ch R = 1 ,19841   ,388,388,388
BEGIN DESCRIPTION:
Elm 02 01 19840.54
END DESCRIPTION:
XS GIS Cut Line= 3
      1611212.85      6821618.01      1611262.76      6822392.72
      1611260.59       6822920.1
#Sta/Elev= 30
  4228.1 1812.04  4348.3 1810.86  4418.5  1811.2  4528.7 1810.63  4538.7 1811.02
  4608.9  1810.7  4647.1 1810.75    4659 1811.13  4709.1 1810.74  4719.1 1811.12
  4869.4    1811  4899.5 1810.14  4909.5  1810.7  4939.6  1809.9  4969.6 1810.31
  4977.6  1809.7  4977.9  1809.2  4981.4  1809.2  4981.6  1809.7  4999.5 1810.54
  5049.7 1810.08  5069.7  1810.3  5089.7 1810.68  5109.7 1811.64  5199.7 1813.78
  5229.7  1813.8  5409.7 1816.13  5439.7 1816.02  5509.7 1817.03  5531.8 1816.91
#Mann= 3 ,-1 , 0
  4228.1     .05       0  4977.6     .03       0  4981.6     .05       0
Bank Sta=4977.6,4981.6
XS Rating Curve= 0 ,0
Exp/Cntr=0.3,0.1

Type RM Length L Ch R = 1 ,19453   ,621,621,621
BEGIN DESCRIPTION:
Elm 02 01 19453.49
END DESCRIPTION:
XS GIS Cut Line= 6
      1611188.66      6821610.45       1611212.1      6822224.99
      1611139.07      6822227.79      1611002.35      6822284.21
      1610909.03      6822288.55      1610301.42      6822444.79
#Sta/Elev= 30
  4073.9 1811.64  4231.6 1810.66  4291.6 1811.12  4311.6 1810.54  4681.9 1810.65
    4706    1810    4736 1810.09    4746 1812.51  4761.5 1813.98  4833.6  1813.7
  4839.3 1813.27  4910.5 1814.47  4937.9 1813.58  4987.9 1808.94    4996 1807.61
  4996.2 1807.11  4999.7 1807.11    5000 1807.61  5028.7 1810.25  5111.3 1811.03
  5121.7 1810.59  5152.6 1811.27  5180.4 1810.92  5235.2 1811.61  5261.9 1810.56
  5317.8 1811.83  5359.1 1811.02  5384.1 1811.86  5617.3 1812.55  5631.3 1813.22
#Mann= 3 ,-1 , 0
  4073.9     .05       0    4996     .03       0    5000     .05       0
Bank Sta=4996,5000
XS Rating Curve= 0 ,0
Exp/Cntr=0.3,0.1

Type RM Length L Ch R = 1 ,18832   ,421,421,421
BEGIN DESCRIPTION:
Elm 02 01 18831.62
END DESCRIPTION:
XS GIS Cut Line= 3
      1611144.06      6821624.81      1611026.87       6821865.7
      1610534.67      6822286.29
#Sta/Elev= 30
  4735.2 1811.21  4872.2 1809.83  4907.8 1809.76  4924.8 1810.28  4930.4 1809.87
  4947.3 1809.76  4961.2 1808.77  4969.9 1807.83  4975.5 1806.75  4983.4 1806.43
  4992.4 1806.37  5001.6 1807.28  5105.4 1807.34  5154.8 1808.06  5197.7 1807.87
  5310.7 1808.73  5339.3 1808.32  5388.7 1808.56  5408.6 1806.37  5408.8 1805.87
  5412.4 1805.87  5412.7 1806.37  5417.2 1808.13  5431.5 1808.38  5502.9 1809.03
  5517.1 1809.48  5552.2 1809.25  5558.8 1809.69  5580.8 1809.53  5650.5 1810.29
#Mann= 3 ,-1 , 0
  4735.2     .05       0  5408.6     .05       0  5412.7     .05       0
Bank Sta=5408.6,5412.7
XS Rating Curve= 0 ,0
Exp/Cntr=0.3,0.1

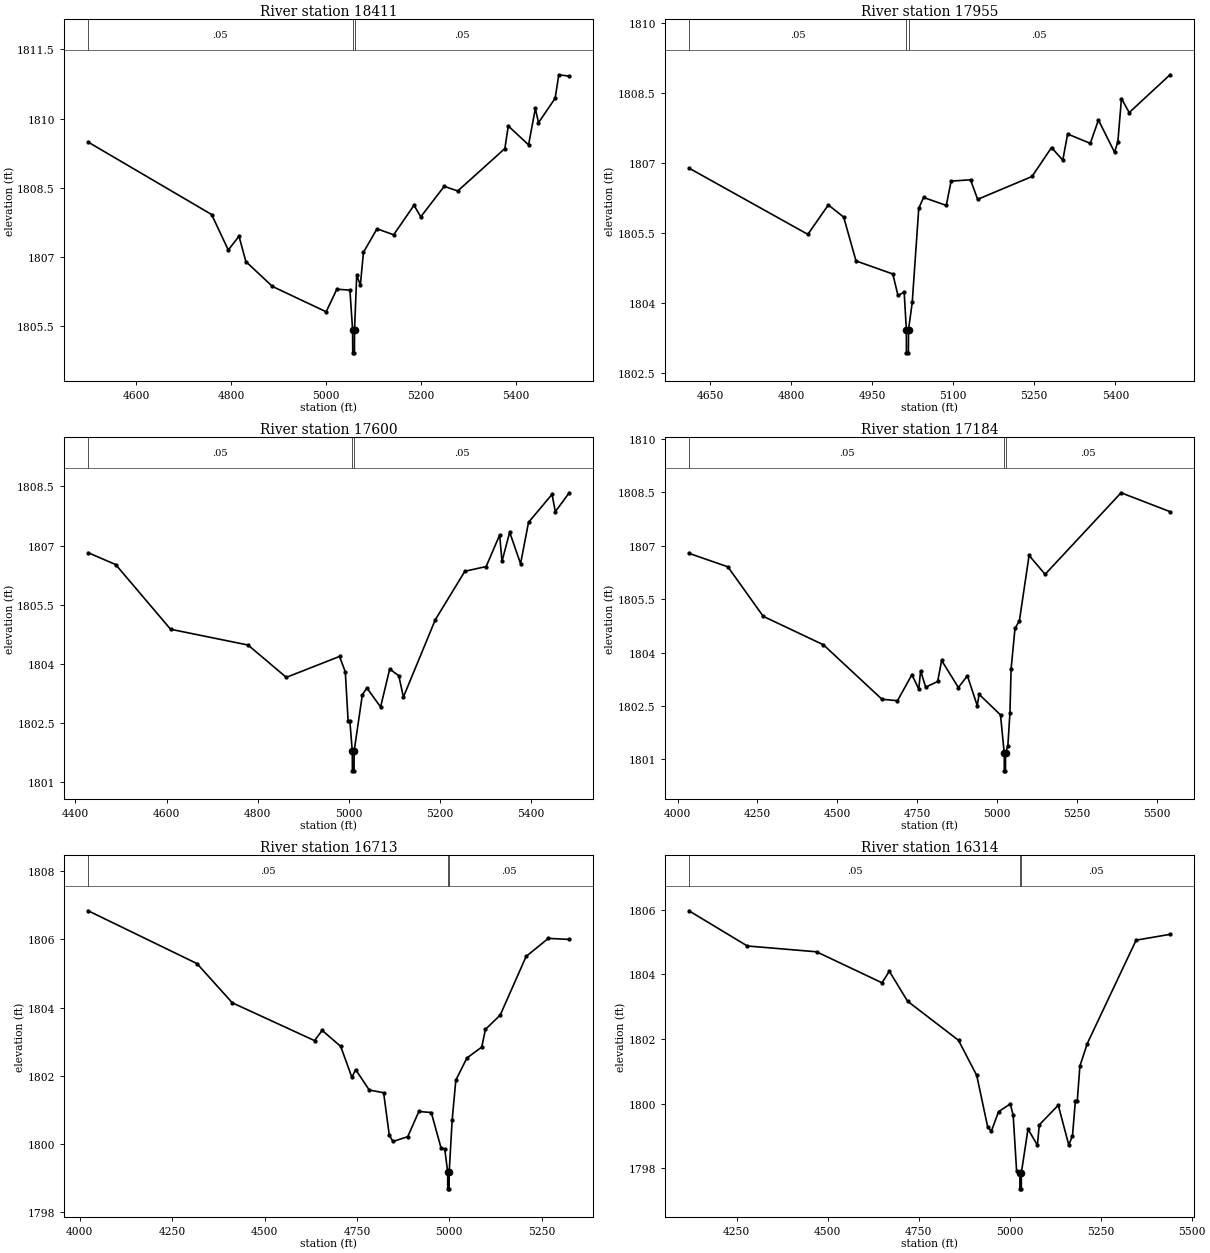
Type RM Length L Ch R = 1 ,18411   ,456,456,456
BEGIN DESCRIPTION:
Elm 02 01 18411.36
END DESCRIPTION:
XS GIS Cut Line= 3
      1610959.18      6821536.25      1610647.96      6821932.11
      1610317.22      6822321.44
#Sta/Elev= 30
  4498.4 1809.49  4758.7 1807.92  4793.9 1807.15  4816.5 1807.45  4830.9  1806.9
    4887 1806.36  5000.3 1805.81  5022.8  1806.3  5050.4 1806.28    5056 1805.42
  5056.3 1804.92  5059.9 1804.92  5060.1 1805.42  5064.7  1806.6  5072.4 1806.39
  5078.9  1807.1  5107.5 1807.61  5142.6 1807.48  5185.5 1808.12  5199.8 1807.87
  5249.2 1808.53  5277.7 1808.43  5377.1 1809.35  5384.3 1809.84  5427.1 1809.43
  5441.4 1810.22    5448 1809.91  5483.1 1810.44  5490.8 1810.95  5512.8 1810.92
#Mann= 3 ,-1 , 0
  4498.4     .05       0    5056     .05       0  5060.1     .05       0
Bank Sta=5056,5060.1
XS Rating Curve= 0 ,0
Exp/Cntr=0.3,0.1

Type RM Length L Ch R = 1 ,17955   ,355,355,355
BEGIN DESCRIPTION:
Elm 02 01 17954.53
END DESCRIPTION:
XS GIS Cut Line= 3
      1610604.11      6821407.12      1610416.41      6821748.88
      1610135.37      6822162.29
#Sta/Elev= 30
  4611.2  1806.9  4831.1 1805.48    4869 1806.11  4897.4 1805.85  4920.2 1804.91
  4988.3 1804.63  4997.8 1804.17  5009.3 1804.24  5013.3 1803.44  5013.5 1802.94
  5017.1 1802.94  5017.4 1803.44  5024.2 1804.02  5036.3 1806.04  5045.2 1806.27
  5087.2  1806.1  5096.1 1806.62    5132 1806.65  5145.2 1806.23  5245.8 1806.72
  5281.8 1807.34  5302.7 1807.07  5311.6 1807.63  5353.6 1807.43  5368.6 1807.93
  5398.4 1807.24  5404.5 1807.46  5411.2 1808.39  5425.5 1808.09    5501  1808.9
#Mann= 3 ,-1 , 0
  4611.2     .05       0  5013.3     .05       0  5017.4     .05       0
Bank Sta=5013.3,5017.4
XS Rating Curve= 0 ,0
Exp/Cntr=0.3,0.1

Type RM Length L Ch R = 1 ,17600   ,416,416,416
BEGIN DESCRIPTION:
Elm 02 01 17599.32
END DESCRIPTION:
XS GIS Cut Line= 5
       1610552.2      6821349.85        1610142.      6821506.11
      1610128.79      6821640.66      1610130.62      6821890.21
      1610072.92       6822114.5
#Sta/Elev= 30
  4428.1 1806.82  4488.5 1806.52  4608.9 1804.88  4778.8 1804.48  4862.8 1803.66
  4979.5 1804.19  4992.2  1803.8  4998.4 1802.55  5002.2 1802.55  5007.5 1801.79
  5007.8 1801.29  5011.4 1801.29  5011.6 1801.79  5029.6 1803.22  5039.6 1803.39
  5069.6 1802.91  5089.6 1803.87  5109.6  1803.7  5119.6 1803.16  5189.6 1805.12
  5254.5 1806.35  5301.2 1806.47  5330.8 1807.27  5335.9  1806.6  5352.8 1807.34
  5376.7 1806.54  5394.1 1807.59  5445.7  1808.3  5452.9 1807.86  5483.4 1808.34
#Mann= 3 ,-1 , 0
  4428.1     .05       0  5007.5     .05       0  5011.6     .05       0
Bank Sta=5007.5,5011.6
XS Rating Curve= 0 ,0
Exp/Cntr=0.3,0.1

Type RM Length L Ch R = 1 ,17184   ,471,471,471
BEGIN DESCRIPTION:
Elm 02 01 17290.47
END DESCRIPTION:
XS GIS Cut Line= 4
      1610573.86      6821291.27      1609972.32      6821426.82
       1609777.2      6821769.26      1609605.34      6822232.77
#Sta/Elev= 30
  4035.7 1806.79  4157.5 1806.41  4268.1 1805.02  4456.5 1804.22  4639.7 1802.69
  4688.2 1802.65  4733.2 1803.38  4754.8 1802.98  4760.5 1803.49  4776.4 1803.03
  4813.8 1803.19  4826.3 1803.78  4878.7 1803.02  4906.9 1803.35  4937.7 1802.51
  4943.5 1802.83  5010.5 1802.25  5022.1 1801.18  5022.4 1800.68    5026 1800.68
  5026.3 1801.18  5033.5 1801.39    5040 1802.31  5043.6 1803.54  5055.8 1804.68
  5069.5 1804.89  5099.9 1806.73    5150  1806.2  5387.7 1808.49  5540.8 1807.96
#Mann= 3 ,-1 , 0
  4035.7     .05       0  5022.1     .05       0  5026.3     .05       0
Bank Sta=5022.1,5026.3
XS Rating Curve= 0 ,0
Exp/Cntr=0.3,0.1

Type RM Length L Ch R = 1 ,16713   ,399,399,399
BEGIN DESCRIPTION:
Elm 02 01 16713.68
END DESCRIPTION:
XS GIS Cut Line= 3
      1610580.35      6821258.72      1609790.22      6821378.64
      1609288.49      6821395.81
#Sta/Elev= 30
    4023 1806.84  4317.4 1805.29  4412.8 1804.14  4635.3 1803.03  4655.9 1803.33
  4706.1 1802.86  4736.4 1801.95  4746.5 1802.18  4783.3 1801.58  4822.2  1801.5
  4837.4 1800.26  4847.4 1800.07  4887.4 1800.21  4917.5 1800.95  4951.1 1800.92
  4977.5 1799.88  4987.5 1799.85  4995.4 1799.18  4995.6 1798.68  4999.3 1798.68
  4999.6 1799.18  5007.5 1800.69  5017.5 1801.87  5047.5 1802.52  5087.6 1802.84
  5097.6 1803.36  5137.6 1803.78  5207.6  1805.5  5267.7 1806.03  5324.2    1806
#Mann= 3 ,-1 , 0
    4023     .05       0  4995.4     .05       0  4999.6     .05       0
Bank Sta=4995.4,4999.6
XS Rating Curve= 0 ,0
Exp/Cntr=0.3,0.1

Type RM Length L Ch R = 1 ,16314   ,307,307,307
BEGIN DESCRIPTION:
Elm 02 01 16313.64
END DESCRIPTION:
XS GIS Cut Line= 3
      1610535.28      6821071.51      1609652.77      6821098.99
      1609221.75      6821181.03
#Sta/Elev= 30
  4118.8 1805.97  4279.2 1804.88  4469.3  1804.7  4649.3 1803.74  4669.3  1804.1
  4719.4 1803.17  4859.4 1801.96  4909.5 1800.87  4939.5 1799.28  4949.5 1799.14
  4969.5 1799.75  5001.7 1799.99  5009.6 1799.64    5019 1797.92  5027.9 1797.86
  5028.2 1797.36  5031.9 1797.36  5032.1 1797.86  5050.4 1799.21  5076.2 1798.71
  5081.3 1799.34  5133.5 1799.95  5162.3 1798.72  5172.5    1799  5180.6 1800.09
  5185.7 1800.08  5192.9 1801.16  5213.2 1801.86  5347.4 1805.06  5440.5 1805.24
#Mann= 3 ,-1 , 0
  4118.8     .05       0  5027.9     .05       0  5032.1     .05       0
Bank Sta=5027.9,5032.1
XS Rating Curve= 0 ,0
Exp/Cntr=0.3,0.1

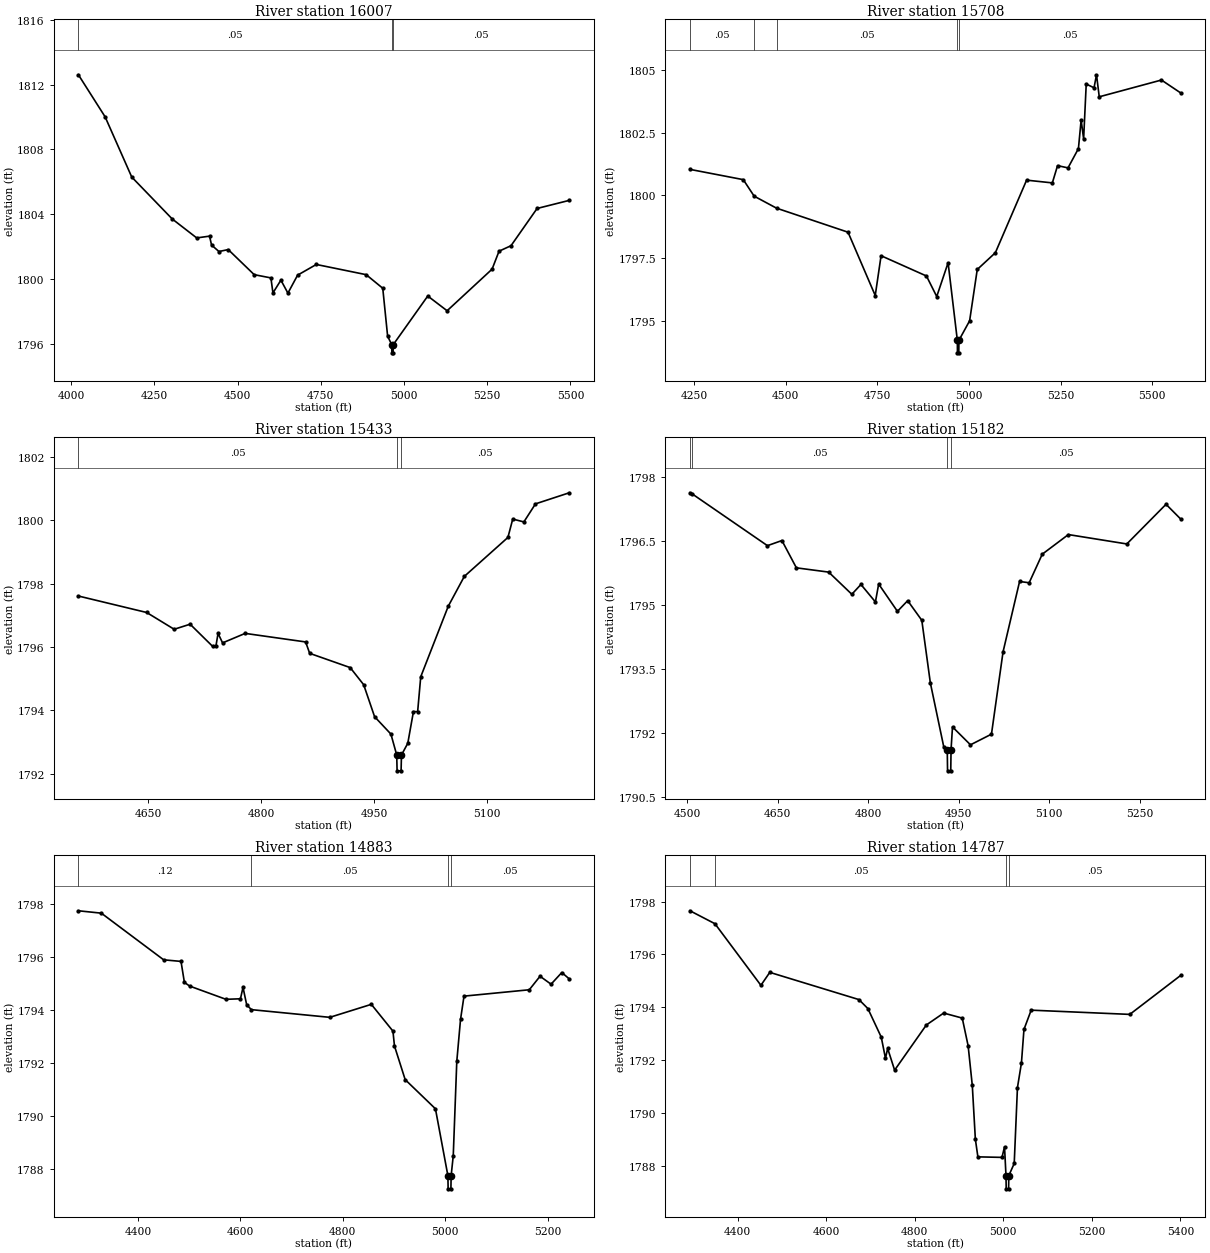
Type RM Length L Ch R = 1 ,16007   ,299,299,299
BEGIN DESCRIPTION:
Elm 02 01 16006.56
END DESCRIPTION:
XS GIS Cut Line= 4
      1610486.66       6820292.5      1609955.45      6820560.84
      1609650.69      6820792.52      1609255.88      6821093.81
#Sta/Elev= 30
    4022 1812.61  4102.3 1810.01  4182.3 1806.29  4303.9  1803.7  4377.4 1802.53
    4416 1802.64    4422 1802.09  4444.2 1801.69  4472.1 1801.81  4550.1 1800.26
  4600.3 1800.06  4606.4 1799.13  4630.3 1799.92  4651.4 1799.12  4680.5 1800.23
  4736.7 1800.89  4886.4 1800.26  4936.3 1799.42  4950.9 1796.46  4963.3 1795.93
  4963.6 1795.43  4967.3 1795.43  4967.6 1795.93  5071.5 1798.94  5129.6 1798.03
  5264.7  1800.6  5285.6 1801.71  5321.6 1802.05  5399.9 1804.35  5496.6 1804.85
#Mann= 3 ,-1 , 0
    4022     .05       0  4963.3     .05       0  4967.6     .05       0
Bank Sta=4963.3,4967.6
XS Rating Curve= 0 ,0
Exp/Cntr=0.3,0.1

Type RM Length L Ch R = 1 ,15708   ,275,275,275
BEGIN DESCRIPTION:
Elm 02 01 16994.478
END DESCRIPTION:
XS GIS Cut Line= 3
      1609890.25       6819883.7      1609513.07      6820544.08
      1609082.99      6820930.53
#Sta/Elev= 30
  4239.5 1801.04  4384.8 1800.63  4414.5 1799.97  4475.6 1799.49  4670.5 1798.53
  4744.7    1796  4760.6 1797.59  4884.4 1796.78  4912.4 1795.96  4943.4 1797.31
  4968.6 1794.21  4968.9 1793.71  4972.6 1793.71  4972.9 1794.21  5002.1 1794.99
  5022.9 1797.04  5072.3 1797.71  5157.5 1800.61  5227.7  1800.5  5241.9 1801.19
  5270.4  1801.1  5298.8 1801.87  5306.2 1803.01    5313 1802.26  5320.1 1804.45
  5341.4  1804.3  5348.1 1804.82  5355.6 1803.94  5525.2 1804.61  5578.2 1804.09
#Mann= 5 ,-1 , 0
  4239.5     .05       0  4414.5     .12       0  4475.6     .05       0
  4968.6     .05       0  4972.9     .05       0
Bank Sta=4968.6,4972.9
XS Rating Curve= 0 ,0
Exp/Cntr=0.3,0.1

Type RM Length L Ch R = 1 ,15433   ,251,251,251
BEGIN DESCRIPTION:
Elm 02 01 15433.09
END DESCRIPTION:
XS GIS Cut Line= 5
      1609577.33      6820105.07      1609422.82      6820202.29
      1609368.04      6820284.21      1609304.22      6820438.28
      1609196.81      6820611.87
#Sta/Elev= 30
  4556.9 1797.61  4647.6 1797.09  4684.1 1796.56  4705.3 1796.72  4735.2 1796.02
  4739.5 1796.02  4742.4 1796.43  4748.4 1796.13  4778.4 1796.43  4858.7 1796.16
  4864.1  1795.8  4917.9 1795.35  4935.8 1794.81  4950.3  1793.8    4972 1793.25
  4979.7 1792.59  4980.2 1792.09  4985.5 1792.09    4986 1792.59  4994.4 1792.96
  5001.9 1793.96  5007.5 1793.96  5011.6 1795.06  5048.2 1797.29  5069.5 1798.23
  5127.4 1799.46  5133.8 1800.04  5148.6 1799.95    5164 1800.52  5208.9 1800.87
#Mann= 3 ,-1 , 0
  4556.9     .05       0  4979.7     .05       0    4986     .05       0
Bank Sta=4979.7,4986
XS Rating Curve= 0 ,0
Exp/Cntr=0.3,0.1

Type RM Length L Ch R = 1 ,15182   ,299,299,299
BEGIN DESCRIPTION:
Elm 02 01 15181.72
END DESCRIPTION:
XS GIS Cut Line= 4
      1609563.45      6820096.39      1609214.48      6820238.75
      1609105.66      6820290.71      1608830.02      6820445.89
#Sta/Elev= 30
  4504.7 1797.63  4507.7 1797.61  4633.1 1796.39  4657.1 1796.51  4681.1 1795.87
  4734.6 1795.77    4773 1795.25  4788.1 1795.48  4812.1 1795.07  4817.5 1795.49
  4848.6 1794.85  4865.6  1795.1    4889 1794.64  4903.2 1793.17  4925.3 1791.68
  4931.2 1791.61  4931.7 1791.11    4937 1791.11  4937.5 1791.61  4939.9 1792.14
  4969.7 1791.72  5004.5 1791.97  5023.7  1793.9  5051.1 1795.55    5067 1795.52
  5088.7 1796.19    5132 1796.65  5228.9 1796.43  5293.9 1797.36  5318.5 1797.01
#Mann= 4 ,-1 , 0
  4504.7     .12       0  4507.7     .05       0  4931.2     .05       0
  4937.5     .05       0
Bank Sta=4931.2,4937.5
XS Rating Curve= 0 ,0
Exp/Cntr=0.3,0.1

Type RM Length L Ch R = 1 ,14883   ,96,96,96
BEGIN DESCRIPTION:
Elm 02 01 14883.48
END DESCRIPTION:
XS GIS Cut Line= 4
      1609539.16        6820020.      1608933.38      6820121.93
      1608848.49       6820182.2      1608672.71      6820346.05
#Sta/Elev= 30
  4283.8 1797.76  4328.6 1797.67  4450.3 1795.91  4484.2 1795.85  4490.8 1795.06
    4501 1794.92    4572 1794.42  4600.3 1794.44  4605.3 1794.87  4612.5 1794.21
  4621.7 1794.03  4774.8 1793.74  4855.9 1794.23  4898.1 1793.22  4901.1 1792.66
    4922 1791.39  4981.1 1790.29  5005.4 1787.77  5005.9 1787.27  5011.3 1787.27
  5011.8 1787.77  5015.9 1788.52  5022.8 1792.08  5030.1 1793.66  5036.9 1794.54
  5164.4 1794.78  5185.4 1795.29  5206.9 1794.99  5227.9 1795.43  5242.5 1795.19
#Mann= 4 ,-1 , 0
  4283.8     .12       0  4621.7     .05       0  5005.4     .05       0
  5011.8     .05       0
Bank Sta=5005.4,5011.8
XS Rating Curve= 0 ,0
Exp/Cntr=0.3,0.1

Type RM Length L Ch R = 1 ,14787   ,335,335,335
BEGIN DESCRIPTION:
Elm 02 01 15042.487
END DESCRIPTION:
XS GIS Cut Line= 4
      1609494.04      6819980.06      1608898.51      6820051.25
      1608551.07      6820236.59      1608508.23      6820343.79
#Sta/Elev= 30
  4292.2 1797.65  4348.6 1797.16  4452.4 1794.83  4472.5 1795.32  4673.9 1794.29
  4694.1 1793.95  4724.3 1792.87  4733.8 1792.07  4738.8 1792.44  4754.5 1791.62
  4826.2 1793.33  4865.3 1793.78  4907.3 1793.59  4920.6 1792.54    4930 1791.04
  4936.9 1789.01  4942.6 1788.34  4997.1 1788.32  5002.8 1788.72  5006.1 1787.63
  5006.6 1787.13    5012 1787.13  5012.5 1787.63  5024.7 1788.09    5032 1790.96
    5041 1791.89  5046.7 1793.16    5063 1793.89  5285.8 1793.73  5401.2 1795.21
#Mann= 4 ,-1 , 0
  4292.2     .12       0  4348.6     .05       0  5006.1     .05       0
  5012.5     .05       0
Bank Sta=5006.1,5012.5
XS Rating Curve= 0 ,0
Exp/Cntr=0.3,0.1