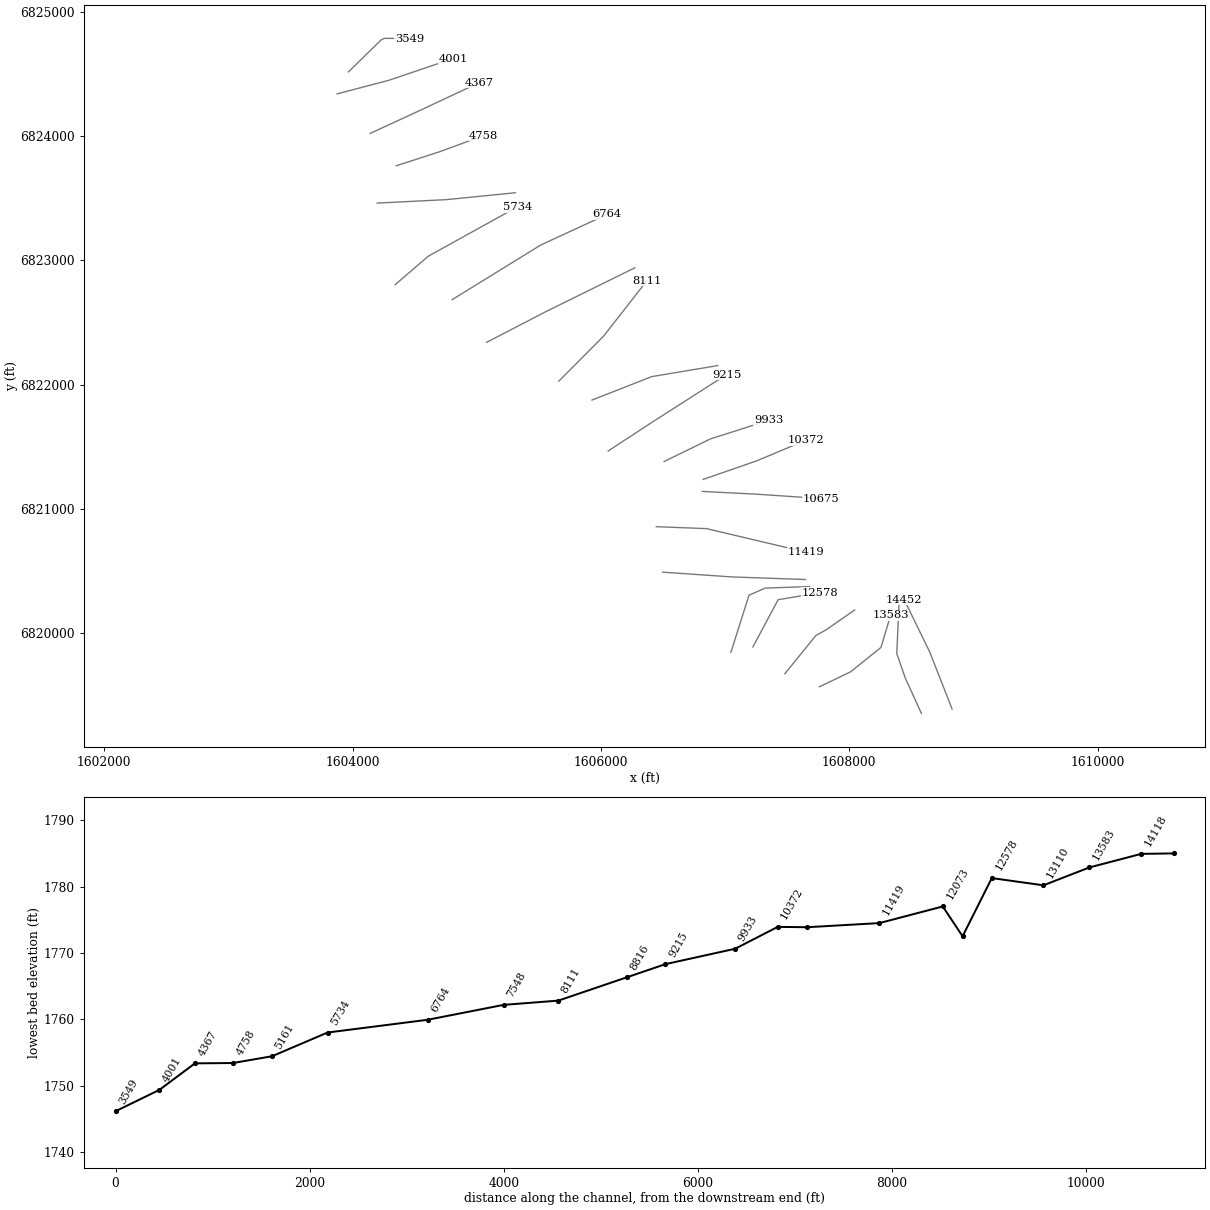
HEC-RAS study Elm 02 01.prj: Elm 02 01 Base Level Engineering

--- Elm 02 01.g01 (geometry) --- (continued)

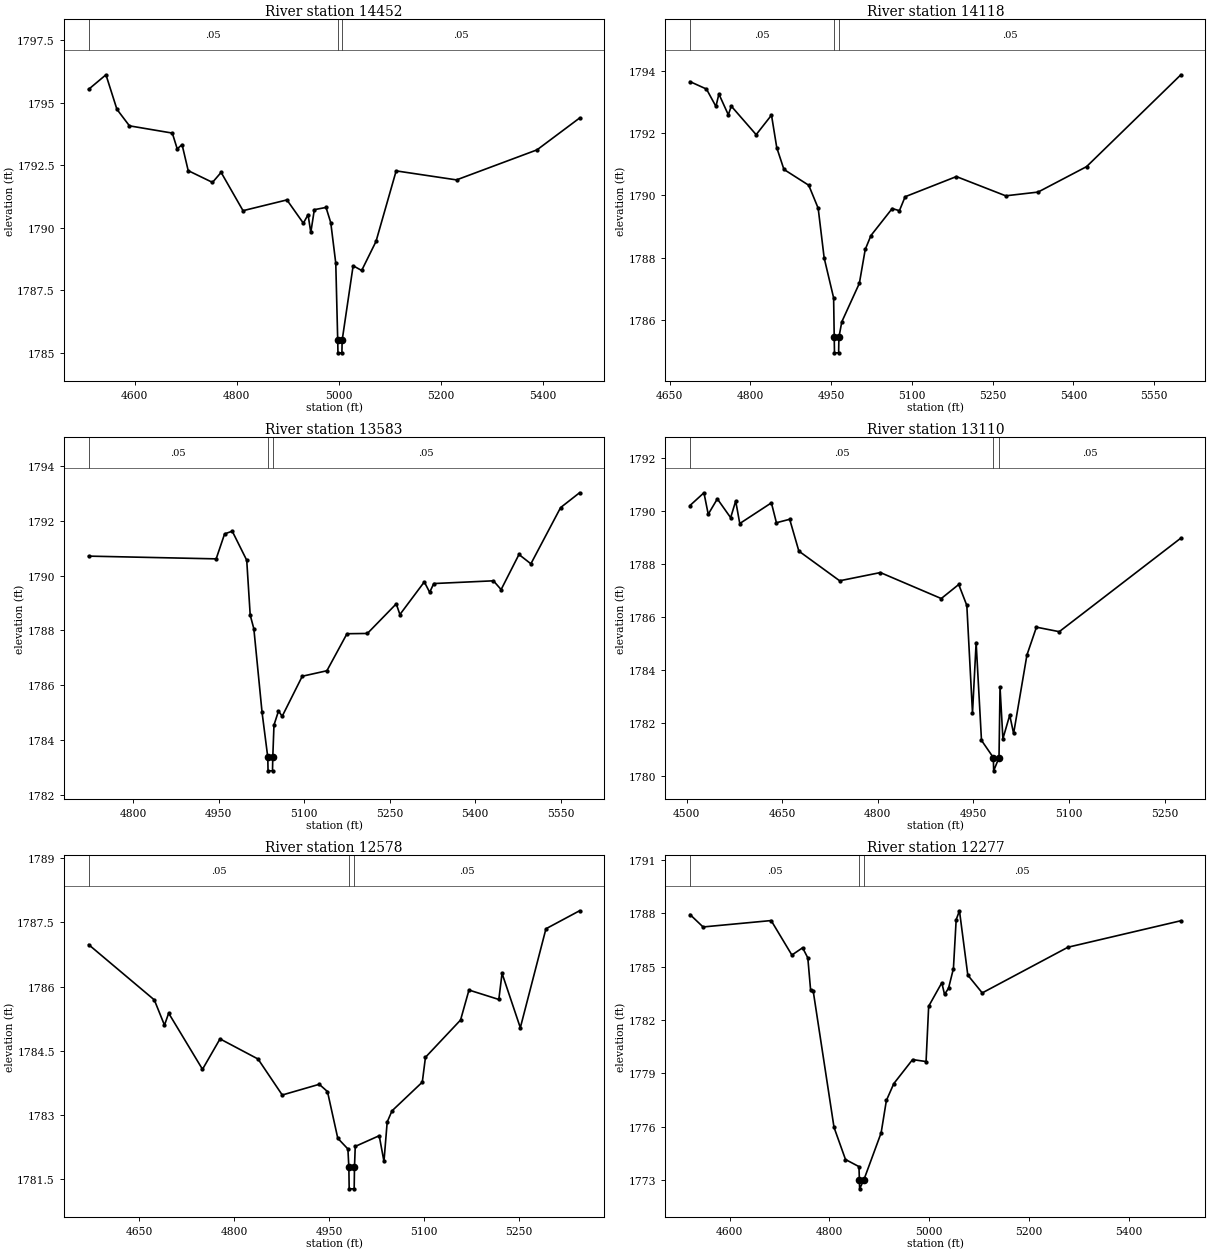
Type RM Length L Ch R = 1 ,14452   ,334,334,334
BEGIN DESCRIPTION:
Elm 02 01 14452.2
END DESCRIPTION:
XS GIS Cut Line= 3
      1608828.28      6819386.43      1608648.61      6819844.73
      1608442.89      6820266.58
#Sta/Elev= 30
  4509.7 1795.53  4543.6 1796.11  4565.1 1794.73  4589.6 1794.07  4673.6 1793.78
  4683.2 1793.15  4692.7 1793.32  4704.7 1792.28  4752.3 1791.81  4769.2 1792.21
  4812.1 1790.68  4898.1 1791.11  4930.3 1790.18  4939.5 1790.52  4944.9 1789.81
  4951.8 1790.72  4974.7 1790.81    4984  1790.2  4993.8 1788.58  4997.6  1785.5
  4998.1    1785  5005.8    1785  5006.3  1785.5  5027.8 1788.48  5044.5 1788.29
  5072.6 1789.45  5112.1 1792.27  5230.3 1791.91    5388 1793.11  5471.3 1794.38
#Mann= 3 ,-1 , 0
  4509.7     .05       0  4997.6     .05       0  5006.3     .05       0
Bank Sta=4997.6,5006.3
XS Rating Curve= 0 ,0
Exp/Cntr=0.3,0.1

Type RM Length L Ch R = 1 ,14118   ,535,535,535
BEGIN DESCRIPTION:
Elm 02 01 14118.32
END DESCRIPTION:
XS GIS Cut Line= 4
      1608580.89      6819351.27      1608450.69       6819637.7
      1608382.78       6819834.2      1608400.25      6820223.07
#Sta/Elev= 30
  4687.9 1793.67  4718.5 1793.43  4736.1 1792.87  4741.6 1793.27  4759.1  1792.6
  4764.6 1792.88  4810.8 1791.96  4839.3 1792.59  4849.1 1791.54  4862.4 1790.84
  4908.5 1790.33    4926 1789.59  4937.1 1787.99  4954.7  1786.7  4955.8 1785.43
  4956.3 1784.93    4964 1784.93  4964.5 1785.43  4969.9 1785.93  5002.5 1787.17
  5013.4 1788.26    5024 1788.71  5063.5 1789.58  5076.9 1789.51  5087.5 1789.96
  5182.7 1790.61  5274.3 1789.99  5334.4 1790.11  5424.5 1790.93  5599.7 1793.89
#Mann= 3 ,-1 , 0
  4687.9     .05       0  4955.8     .05       0  4964.5     .05       0
Bank Sta=4955.8,4964.5
XS Rating Curve= 0 ,0
Exp/Cntr=0.3,0.1

Type RM Length L Ch R = 1 ,13583   ,473,473,473
BEGIN DESCRIPTION:
Elm 02 01 13583.17
END DESCRIPTION:
XS GIS Cut Line= 4
      1607759.97      6819565.58      1608009.94      6819685.35
      1608255.76      6819882.48      1608332.54      6820139.79
#Sta/Elev= 30
    4722 1790.71  4945.6 1790.61  4960.4 1791.52  4973.8 1791.62  4999.2 1790.56
  5005.3 1788.56  5011.7 1788.06  5026.1 1785.01  5036.1 1783.38  5036.6 1782.88
  5044.4 1782.88  5044.9 1783.38    5047 1784.55  5054.9 1785.06  5061.4 1784.87
  5096.6 1786.33  5139.8 1786.53    5175 1787.88  5210.8 1787.89  5261.4 1788.97
  5267.8 1788.58  5310.6 1789.77    5320 1789.39  5327.2 1789.71  5431.8 1789.81
  5445.3 1789.49  5476.6 1790.77  5497.5 1790.43  5549.6 1792.48  5582.8 1793.02
#Mann= 3 ,-1 , 0
    4722     .05       0  5036.1     .05       0  5044.9     .05       0
Bank Sta=5036.1,5044.9
XS Rating Curve= 0 ,0
Exp/Cntr=0.3,0.1

Type RM Length L Ch R = 1 ,13110   ,532,532,532
BEGIN DESCRIPTION:
Elm 02 01 13109.83
END DESCRIPTION:
XS GIS Cut Line= 4
      1607481.83      6819671.02      1607730.48      6819977.46
      1607817.72      6820027.05      1608043.68      6820184.01
#Sta/Elev= 30
  4505.4  1790.2  4527.3 1790.68    4534 1789.87  4548.3 1790.45  4569.2 1789.74
  4577.1 1790.37  4583.5 1789.52  4633.1  1790.3    4641 1789.55  4661.8 1789.68
  4676.2 1788.48  4740.2 1787.36  4804.1 1787.67  4899.6 1786.69    4927 1787.22
  4939.7 1786.43  4948.6 1782.37  4954.3 1785.03  4962.7 1781.34  4981.3 1780.69
  4981.8 1780.19  4990.2 1780.69  4991.8 1783.34  4996.3  1781.4    5007 1782.29
  5013.1  1781.6    5034 1784.56  5048.9 1785.61  5084.7 1785.44  5275.5 1788.97
#Mann= 3 ,-1 , 0
  4505.4     .05       0  4981.3     .05       0  4990.2     .05       0
Bank Sta=4981.3,4990.2
XS Rating Curve= 0 ,0
Exp/Cntr=0.3,0.1

Type RM Length L Ch R = 1 ,12578   ,301,301,301
BEGIN DESCRIPTION:
Elm 02 01 12577.72
END DESCRIPTION:
XS GIS Cut Line= 3
      1607223.97      6819886.42       1607427.1      6820266.63
      1607767.34      6820323.92
#Sta/Elev= 30
  4570.1 1786.98  4673.9 1785.69    4690  1785.1  4696.6 1785.38  4750.1 1784.07
  4777.8 1784.78  4837.9 1784.31  4876.2 1783.47  4934.7 1783.72  4947.7 1783.55
    4964 1782.46    4980 1782.21  4981.5 1781.78    4982 1781.28  4989.9 1781.28
  4990.4 1781.78  4991.6 1782.27  5029.5 1782.52    5037 1781.92  5042.1 1782.84
  5049.7  1783.1  5097.6 1783.77  5102.6 1784.35  5158.1 1785.22  5171.4 1785.92
  5218.6  1785.7  5223.7 1786.31  5252.6 1785.04  5293.1 1787.35  5346.2 1787.77
#Mann= 3 ,-1 , 0
  4570.1     .05       0  4981.5     .05       0  4990.4     .05       0
Bank Sta=4981.5,4990.4
XS Rating Curve= 0 ,0
Exp/Cntr=0.3,0.1

Type RM Length L Ch R = 1 ,12277   ,204,204,204
BEGIN DESCRIPTION:
Elm 02 01 12276.88
END DESCRIPTION:
XS GIS Cut Line= 4
      1607046.88      6819842.99      1607192.72      6820303.09
      1607322.93      6820360.38      1607681.11      6820372.49
#Sta/Elev= 30
  4520.8 1787.93    4547 1787.23  4683.4 1787.59  4724.9 1785.65  4746.4 1786.06
  4756.8 1785.49  4762.4 1783.69  4767.7 1783.61  4809.3 1775.96  4832.3 1774.15
  4859.3 1773.75  4860.1    1773  4860.6  1772.5    4869    1773  4903.7 1775.65
  4914.2 1777.47  4929.1 1778.42  4966.7 1779.77  4993.7 1779.66  4998.9 1782.77
  5025.2 1784.09  5030.7 1783.44  5038.7 1783.78  5048.5 1784.89    5054 1787.64
  5060.6 1788.14  5077.3 1784.52  5106.2 1783.52  5277.9 1786.09  5504.1 1787.58
#Mann= 3 ,-1 , 0
  4520.8     .05       0  4860.1     .05       0    4869     .05       0
Bank Sta=4860.1,4869
XS Rating Curve= 0 ,0
Exp/Cntr=0.3,0.1

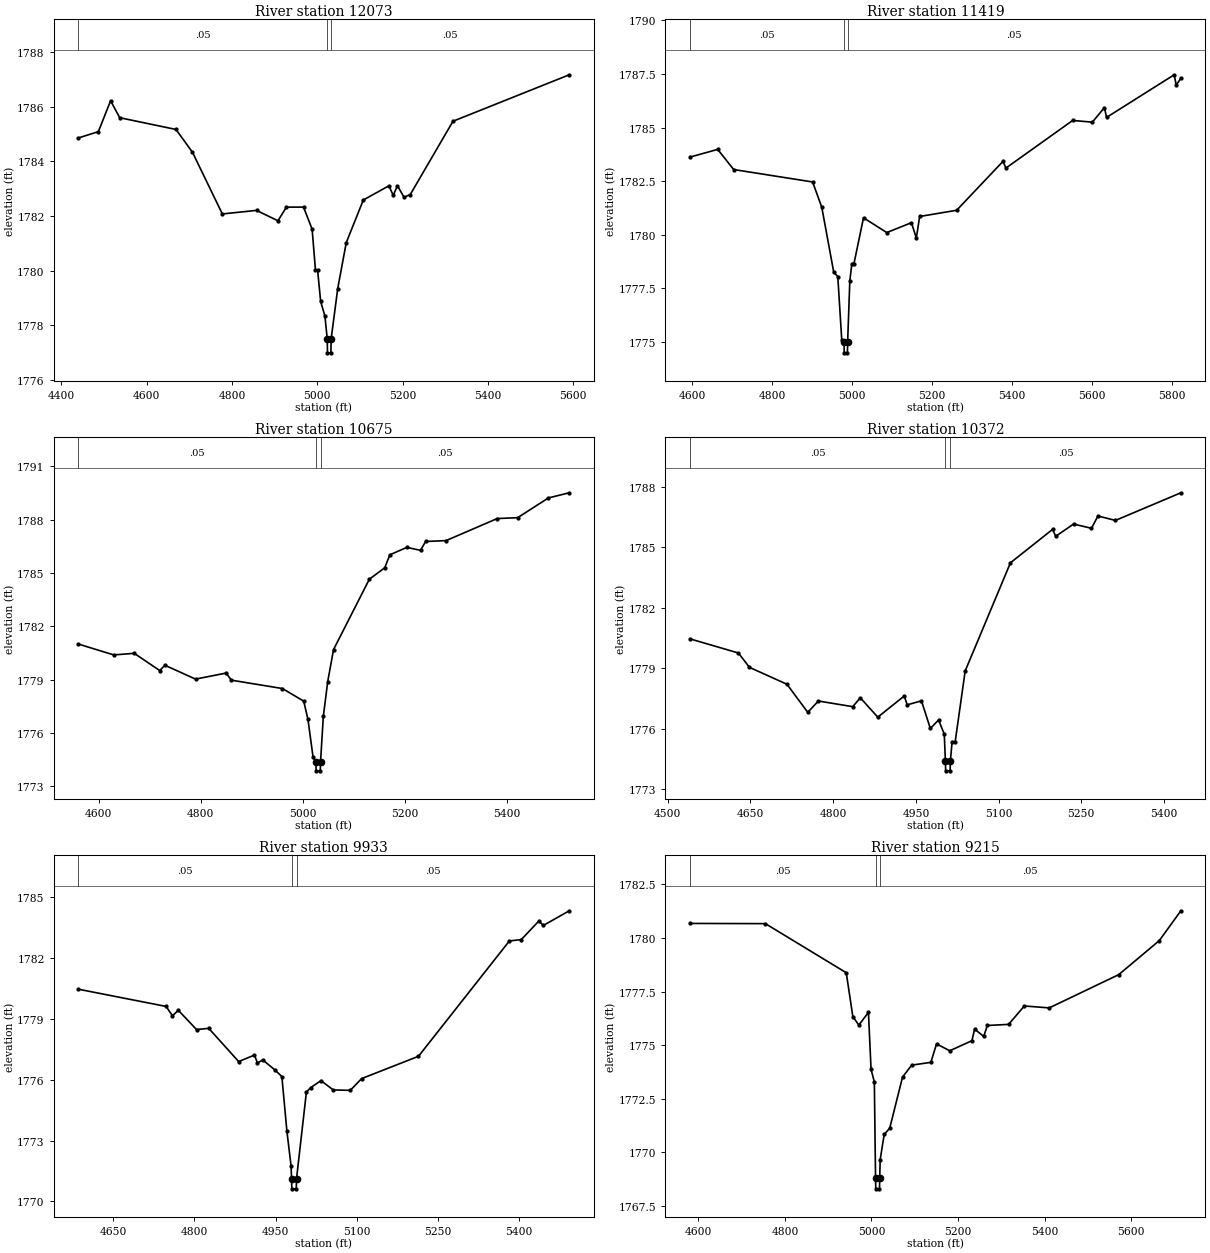
Type RM Length L Ch R = 1 ,12073   ,654,654,654
BEGIN DESCRIPTION:
Elm 02 01 12072.88
END DESCRIPTION:
XS GIS Cut Line= 3
      1606498.33      6820488.42      1607055.57      6820450.23
      1607647.55      6820429.39
#Sta/Elev= 30
  4439.9 1784.86  4486.7 1785.09  4515.4 1786.22  4536.8  1785.6  4668.7 1785.17
  4707.2 1784.34  4777.4 1782.08  4857.6 1782.21  4907.7 1781.83  4927.7 1782.33
  4967.8 1782.33  4987.9 1781.52  4995.7 1780.03  5000.7 1780.03  5007.9 1778.88
  5017.9 1778.34  5023.4  1777.5  5023.9    1777  5031.9    1777  5032.4  1777.5
  5047.9 1779.35  5067.9 1781.03  5107.9 1782.59    5168 1783.11    5178 1782.76
    5188 1783.11  5203.4 1782.69    5218 1782.79  5318.1 1785.47  5590.8 1787.17
#Mann= 3 ,-1 , 0
  4439.9     .05       0  5023.4     .05       0  5032.4     .05       0
Bank Sta=5023.4,5032.4
XS Rating Curve= 0 ,0
Exp/Cntr=0.3,0.1

Type RM Length L Ch R = 1 ,11419   ,744,744,744
BEGIN DESCRIPTION:
Elm 02 01 11419.17
END DESCRIPTION:
XS GIS Cut Line= 3
      1606445.83      6820854.91      1606850.36      6820839.29
      1607650.37      6820650.13
#Sta/Elev= 30
  4595.2 1783.62  4664.4 1783.98  4704.4 1783.04  4901.7 1782.46  4924.6 1781.28
  4954.6 1778.24  4964.6 1778.05  4974.6 1775.07  4980.2 1774.99  4980.7 1774.49
  4988.7 1774.49  4989.2 1774.99  4994.7 1777.86  4999.8 1778.65    5005 1778.65
  5028.9 1780.79    5087  1780.1  5148.7 1780.56  5160.9 1779.84  5169.2 1780.85
  5261.7 1781.14  5377.4 1783.42    5385 1783.11  5551.7 1785.33  5600.8 1785.25
  5631.1 1785.93  5636.3 1785.47  5805.4 1787.46  5810.5 1786.98  5822.1  1787.3
#Mann= 3 ,-1 , 0
  4595.2     .05       0  4980.2     .05       0  4989.2     .05       0
Bank Sta=4980.2,4989.2
XS Rating Curve= 0 ,0
Exp/Cntr=0.3,0.1

Type RM Length L Ch R = 1 ,10675   ,303,303,303
BEGIN DESCRIPTION:
Elm 02 01 10674.72
END DESCRIPTION:
XS GIS Cut Line= 3
      1606815.77      6821138.94      1607256.73      6821116.37
      1607775.84      6821081.65
#Sta/Elev= 30
  4560.4    1781  4629.7 1780.39  4669.8 1780.48  4719.8 1779.51  4729.8 1779.81
  4789.9 1779.03    4850 1779.37    4860 1778.97  4960.1  1778.5  5001.9 1777.79
  5010.2 1776.76  5020.2 1774.64  5025.7 1774.37  5026.2 1773.87  5034.3 1773.87
  5034.8 1774.37  5040.3 1776.93  5048.9 1778.89  5060.3 1780.69  5130.5 1784.65
  5160.6 1785.29  5170.6 1786.02    5204 1786.44  5230.7 1786.27  5240.7 1786.77
  5280.8 1786.82    5381 1788.06  5421.1 1788.11  5481.3 1789.22  5522.2 1789.51
#Mann= 3 ,-1 , 0
  4560.4     .05       0  5025.7     .05       0  5034.8     .05       0
Bank Sta=5025.7,5034.8
XS Rating Curve= 0 ,0
Exp/Cntr=0.3,0.1

Type RM Length L Ch R = 1 ,10372   ,439,439,439
BEGIN DESCRIPTION:
Elm 02 01 10372.19
END DESCRIPTION:
XS GIS Cut Line= 3
      1606823.18      6821235.59      1607258.93      6821386.63
      1607654.42      6821553.15
#Sta/Elev= 30
  4540.3 1780.46  4628.1 1779.76  4648.1 1779.05  4716.2 1778.21  4753.9 1776.82
  4773.2 1777.38  4835.5  1777.1  4849.2 1777.54  4880.9 1776.58  4928.9 1777.63
  4934.2 1777.19  4960.1 1777.39  4976.2 1776.02  4991.2 1776.44  5001.5 1775.74
  5003.5 1774.42    5004 1773.92  5012.1 1773.92  5012.6 1774.42  5015.7 1775.37
  5021.1 1775.33  5039.4 1778.87  5121.5 1784.23  5198.1 1785.89  5203.5 1785.54
  5235.9 1786.15  5268.5 1785.94  5280.2 1786.55  5311.9 1786.33  5430.6  1787.7
#Mann= 3 ,-1 , 0
  4540.3     .05       0  5003.5     .05       0  5012.6     .05       0
Bank Sta=5003.5,5012.6
XS Rating Curve= 0 ,0
Exp/Cntr=0.3,0.1

Type RM Length L Ch R = 1 ,9933    ,718,718,718
BEGIN DESCRIPTION:
Elm 02 01 9933.35
END DESCRIPTION:
XS GIS Cut Line= 3
      1606508.91      6821379.67      1606882.19      6821561.97
      1607350.49      6821711.13
#Sta/Elev= 30
  4585.6 1780.47  4747.7 1779.62  4759.3 1779.16  4770.2 1779.43  4803.8 1778.48
  4826.4 1778.54  4881.7  1776.9  4910.9 1777.22  4916.4 1776.83  4926.2 1776.98
  4948.5 1776.49  4961.5 1776.16  4970.8 1773.47  4978.5 1771.75  4979.4 1771.12
  4979.9 1770.62  4988.1 1770.62  4988.6 1771.12  5006.8 1775.39  5014.5 1775.61
  5033.8 1775.96  5056.4  1775.5  5087.9 1775.48  5108.9 1776.06  5213.9 1777.16
  5381.8 1782.85  5403.9 1782.92  5436.1 1783.83  5444.8 1783.62  5492.5 1784.34
#Mann= 3 ,-1 , 0
  4585.6     .05       0  4979.4     .03       0  4988.6     .05       0
Bank Sta=4979.4,4988.6
XS Rating Curve= 0 ,0
Exp/Cntr=0.3,0.1

Type RM Length L Ch R = 1 ,9215    ,399,399,399
BEGIN DESCRIPTION:
Elm 02 01 9215.33
END DESCRIPTION:
XS GIS Cut Line= 3
      1606058.42      6821464.74        1606410.      6821694.79
      1607011.68      6822080.03
#Sta/Elev= 30
  4580.6 1780.68  4754.9 1780.67  4941.8 1778.38    4957 1776.33  4970.9 1775.94
  4993.1 1776.53  4999.1 1773.87  5006.7 1773.29  5009.5  1768.8    5010  1768.3
  5018.6  1768.3  5019.1  1768.8  5020.2 1769.66  5029.5 1770.84  5042.3 1771.13
  5071.8 1773.51    5093 1774.07  5137.3  1774.2  5150.5 1775.06  5180.9 1774.74
  5232.3 1775.21  5238.4 1775.75  5259.5 1775.41  5267.9 1775.92    5317 1775.97
  5353.4 1776.83  5410.9 1776.74  5571.5 1778.29  5665.4 1779.88  5715.2 1781.27
#Mann= 3 ,-1 , 0
  4580.6     .05       0  5009.5     .05       0  5019.1     .05       0
Bank Sta=5009.5,5019.1
XS Rating Curve= 0 ,0
Exp/Cntr=0.3,0.1

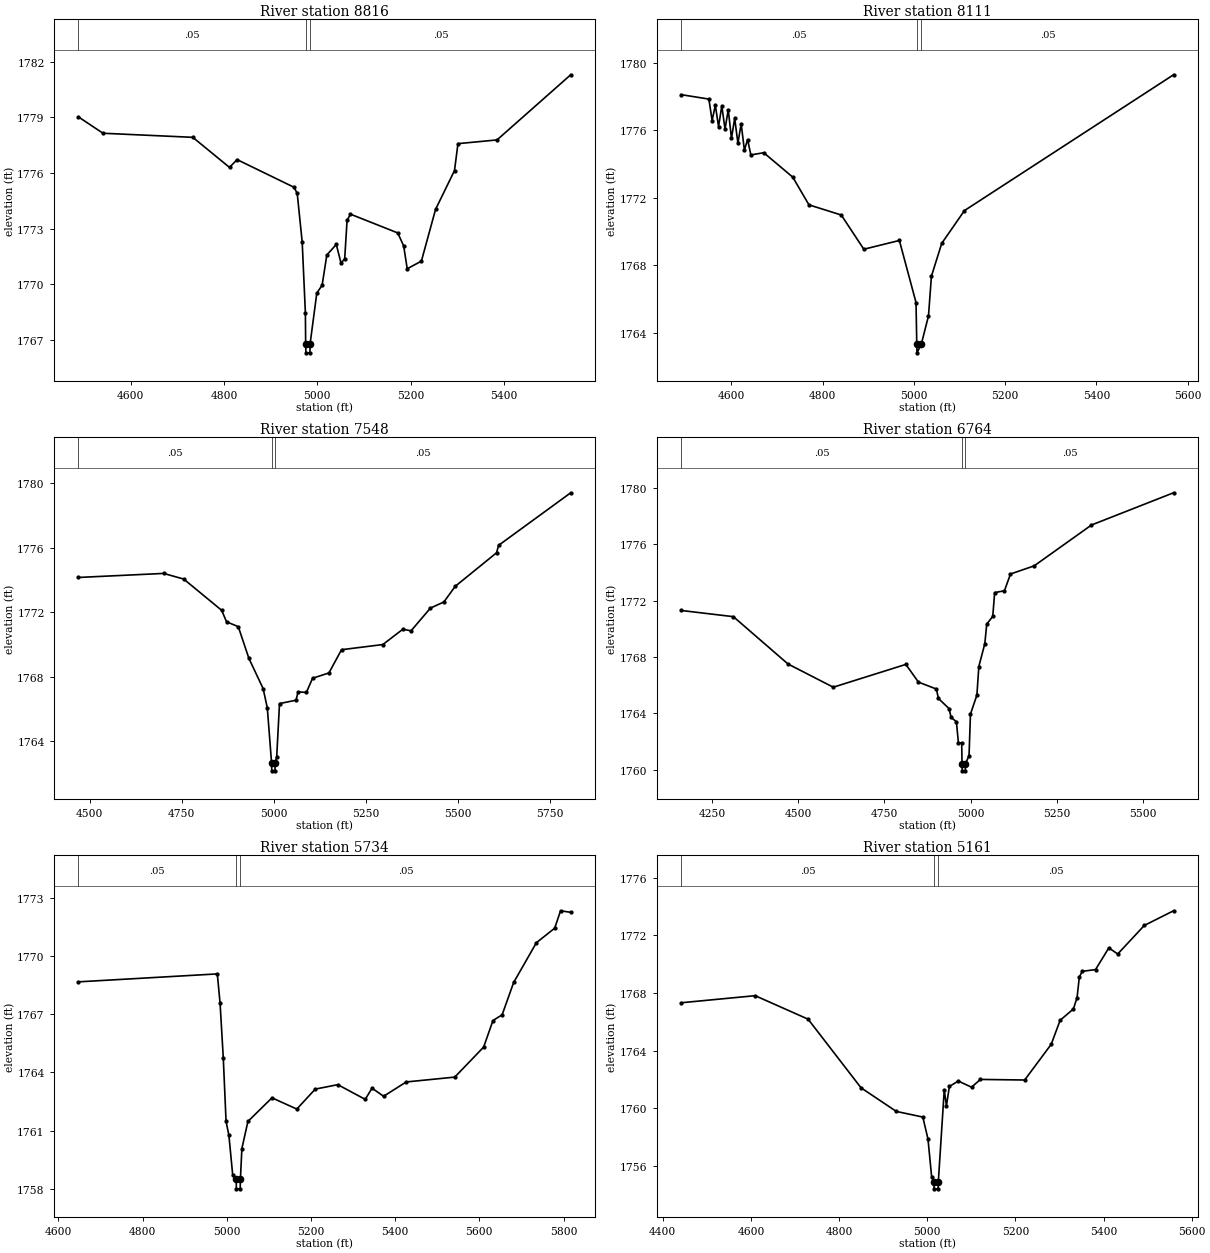
Type RM Length L Ch R = 1 ,8816    ,705,705,705
BEGIN DESCRIPTION:
Elm 02 01 8815.6
END DESCRIPTION:
XS GIS Cut Line= 3
      1605928.26      6821874.92        1606410.      6822063.71
       1606940.8      6822152.54
#Sta/Elev= 30
  4487.9 1779.02  4540.5 1778.14  4733.1 1777.92  4811.8  1776.3  4828.1 1776.72
  4950.1 1775.23    4957  1774.9  4967.7 1772.27  4974.5 1768.47  4975.1 1766.81
  4975.6 1766.31  4984.2 1766.31  4984.7 1766.81    4999 1769.53  5010.4 1769.95
  5020.5 1771.58  5040.8 1772.15  5050.9 1771.15  5058.8 1771.37  5063.9 1773.44
  5071.2 1773.78  5172.6 1772.77  5185.3 1772.07  5192.9 1770.84  5223.3 1771.25
  5253.7 1774.04  5294.3 1776.13  5301.7 1777.58  5385.5 1777.78  5543.5 1781.29
#Mann= 3 ,-1 , 0
  4487.9     .05       0  4975.1     .05       0  4984.7     .05       0
Bank Sta=4975.1,4984.7
XS Rating Curve= 0 ,0
Exp/Cntr=0.3,0.1

Type RM Length L Ch R = 1 ,8111    ,563,563,563
BEGIN DESCRIPTION:
Elm 02 01 8110.98
END DESCRIPTION:
XS GIS Cut Line= 3
      1605660.77      6822026.83      1606023.18       6822391.4
      1606370.22      6822836.05
#Sta/Elev= 30
  4490.7  1778.1  4551.1 1777.84  4558.2 1776.57  4565.2 1777.47  4572.3 1776.21
  4579.4 1777.43  4586.5 1776.06  4593.5 1777.21  4600.6 1775.51  4607.6  1776.7
  4614.7 1775.22  4621.8 1776.38  4628.9 1774.81  4635.9 1775.44    4643 1774.53
  4671.3 1774.66  4734.9 1773.21  4770.3 1771.57    4841 1770.97  4890.5 1768.94
  4968.3 1769.46  5004.8 1765.78  5006.4  1763.3  5006.9  1762.8  5016.2  1763.3
  5032.1 1764.99  5038.5 1767.34  5061.1 1769.29  5110.8 1771.23  5568.8 1779.28
#Mann= 3 ,-1 , 0
  4490.7     .05       0  5006.4     .05       0  5016.2     .05       0
Bank Sta=5006.4,5016.2
XS Rating Curve= 0 ,0
Exp/Cntr=0.3,0.1

Type RM Length L Ch R = 1 ,7548    ,784,784,784
BEGIN DESCRIPTION:
Elm 02 01 7547.86
END DESCRIPTION:
XS GIS Cut Line= 3
      1605079.54      6822339.68      1605555.27      6822586.22
      1606274.03      6822940.39
#Sta/Elev= 30
    4470 1774.15  4701.4  1774.4  4755.9 1774.05  4859.1 1772.11  4872.2  1771.4
  4904.1  1771.1    4933 1769.13  4971.6 1767.26    4983 1766.06  4994.5 1762.66
    4995 1762.16  5003.8 1762.16  5004.3 1762.66  5008.5 1763.03  5016.1 1766.33
    5061 1766.54  5066.6 1767.06  5089.1 1767.02  5105.9  1767.9  5150.4 1768.23
  5184.5 1769.67  5296.8 1769.99  5351.1 1770.94  5373.4 1770.84    5426 1772.25
  5462.6 1772.63  5493.4  1773.6  5605.7 1775.68  5611.2 1776.14  5807.1  1779.4
#Mann= 3 ,-1 , 0
    4470     .05       0  4994.5     .05       0  5004.3     .05       0
Bank Sta=4994.5,5004.3
XS Rating Curve= 0 ,0
Exp/Cntr=0.3,0.1

Type RM Length L Ch R = 1 ,6764    ,1030,1030,1030
BEGIN DESCRIPTION:
Elm 02 01 6763.63
END DESCRIPTION:
XS GIS Cut Line= 3
       1604801.8      6822683.45      1605517.07      6823124.42
       1606050.9      6823370.53
#Sta/Elev= 30
  4160.8  1771.3  4311.9 1770.86  4470.3  1767.5  4601.7 1765.85  4812.2 1767.47
  4848.9 1766.21  4900.9 1765.72  4906.8 1765.05  4937.6 1764.33  4943.5  1763.7
  4958.9  1763.4  4964.8 1761.89  4974.3  1761.9  4975.2 1760.41  4975.7 1759.91
  4984.7 1759.91  4985.2 1760.41  4995.6 1760.99  4999.7 1763.94  5018.4 1765.29
    5024 1767.32  5041.4 1768.95  5046.9 1770.33  5064.4 1770.88  5069.9 1772.57
  5098.3  1772.7  5115.8 1773.89  5184.6 1774.47  5350.8 1777.37  5588.9 1779.66
#Mann= 3 ,-1 , 0
  4160.8     .05       0  4975.2     .05       0  4985.2     .05       0
Bank Sta=4975.2,4985.2
XS Rating Curve= 0 ,0
Exp/Cntr=0.3,0.1

Type RM Length L Ch R = 1 ,5734    ,573,573,573
BEGIN DESCRIPTION:
Elm 02 01 5734.16
END DESCRIPTION:
XS GIS Cut Line= 3
      1604343.45      6822804.97      1604610.82      6823034.14
      1605326.06      6823429.95
#Sta/Elev= 30
  4647.5 1768.68  4977.4 1769.09    4984 1767.57  4991.6 1764.75  4998.2 1761.47
  5004.9 1760.76    5014  1758.7  5022.2 1758.49  5022.7 1757.99  5031.8 1757.99
  5032.3 1758.49  5035.8 1760.07  5050.1 1761.47  5107.3 1762.69  5166.3 1762.11
  5210.1 1763.14  5263.7 1763.37  5328.9 1762.61    5345 1763.19  5372.5 1762.77
  5426.3 1763.51  5541.6 1763.76  5610.2 1765.31  5632.4 1766.68  5654.2 1766.98
  5681.6 1768.65  5735.5  1770.7    5779 1771.45    5793 1772.35  5817.1 1772.27
#Mann= 3 ,-1 , 0
  4647.5     .05       0  5022.2     .05       0  5032.3     .05       0
Bank Sta=5022.2,5032.3
XS Rating Curve= 0 ,0
Exp/Cntr=0.3,0.1

Type RM Length L Ch R = 1 ,5161    ,403,403,403
BEGIN DESCRIPTION:
Elm 02 01 5160.6
END DESCRIPTION:
XS GIS Cut Line= 3
      1604197.66      6823461.22      1604756.65        6823489.
       1605311.1      6823544.44
#Sta/Elev= 30
    4442 1767.32  4609.6 1767.81  4729.7 1766.18  4849.8 1761.42  4929.9 1759.78
    4990 1759.39  5001.7 1757.87  5010.1 1755.22  5015.1 1754.91  5015.6 1754.41
  5024.7 1754.41  5025.2 1754.91  5038.6 1761.26  5043.6 1760.18  5050.3 1761.51
  5070.4 1761.89  5100.5 1761.46  5120.6    1762  5221.1 1761.96  5281.4 1764.44
  5301.5  1766.1  5331.7 1766.89    5340 1767.68  5345.1  1769.1  5351.8  1769.5
  5381.9 1769.62  5412.1 1771.13  5432.2  1770.7  5492.5 1772.68  5558.9  1773.7
#Mann= 3 ,-1 , 0
    4442     .05       0  5015.1     .05       0  5025.2     .05       0
Bank Sta=5015.1,5025.2
XS Rating Curve= 0 ,0
Exp/Cntr=0.3,0.1

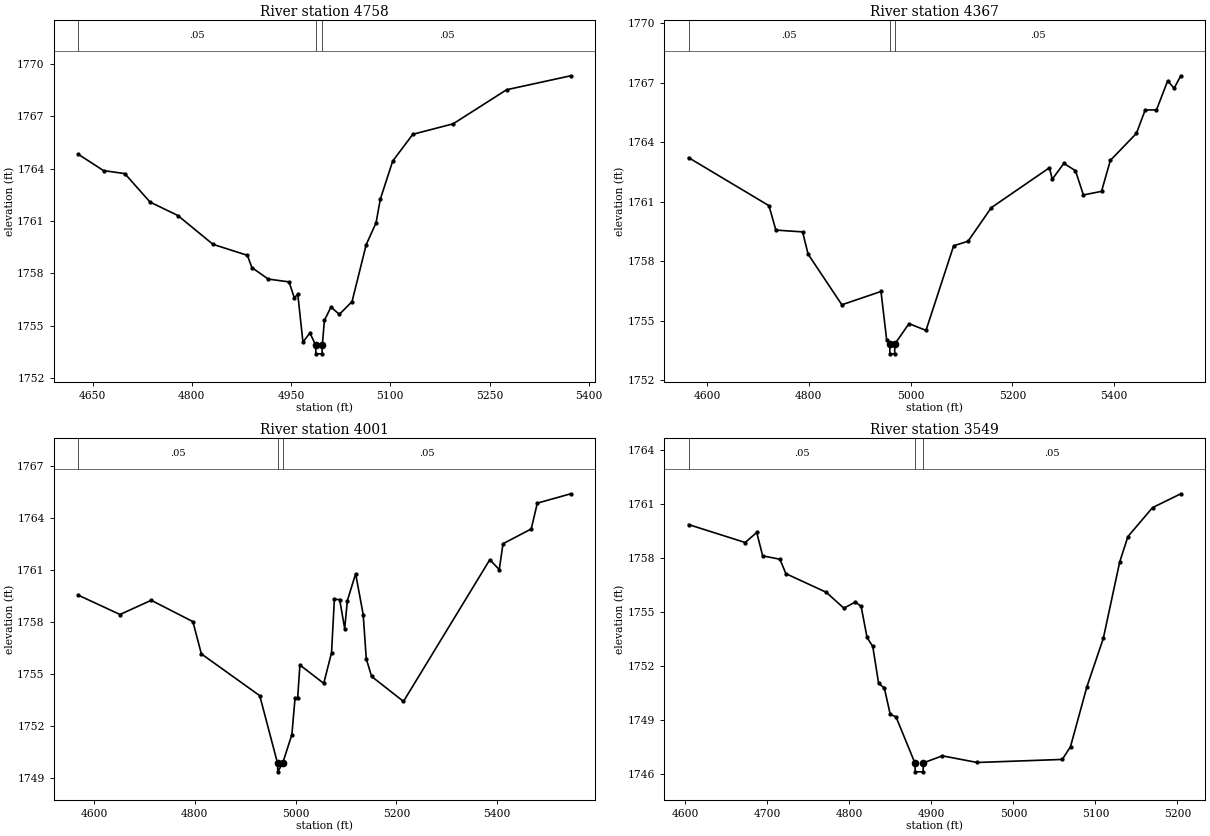
Type RM Length L Ch R = 1 ,4758    ,391,391,391
BEGIN DESCRIPTION:
Elm 02 01 4757.66
END DESCRIPTION:
XS GIS Cut Line= 3
      1604352.08      6823761.93      1604701.46      6823874.78
      1605055.21      6824004.99
#Sta/Elev= 30
  4628.6 1764.81  4666.5 1763.88  4698.6 1763.71  4736.8 1762.08  4778.8 1761.31
  4831.9 1759.66  4883.9 1759.03  4890.7 1758.33  4915.4 1757.67  4946.9 1757.51
  4954.8  1756.6  4960.1  1756.8  4967.9 1754.06  4978.5 1754.59    4987 1753.89
  4987.5 1753.39  4996.7 1753.39  4997.2 1753.89  5000.3  1755.3  5010.2 1756.07
  5022.9 1755.65  5042.1 1756.38  5063.5 1759.64  5078.4 1760.89  5084.8 1762.24
  5103.6 1764.43    5134 1765.96    5195 1766.56  5275.7 1768.51  5372.7 1769.31
#Mann= 3 ,-1 , 0
  4628.6     .05       0    4987     .05       0  4997.2     .05       0
Bank Sta=4987,4997.2
XS Rating Curve= 0 ,0
Exp/Cntr=0.3,0.1

Type RM Length L Ch R = 1 ,4367    ,366,366,366
BEGIN DESCRIPTION:
Elm 02 01 4366.83
END DESCRIPTION:
XS GIS Cut Line= 3
      1604141.55      6824022.34      1604536.53      6824204.64
      1605018.27      6824430.32
#Sta/Elev= 30
  4563.8 1763.22  4721.8  1760.8  4735.4 1759.57  4787.9 1759.48  4798.7 1758.36
    4865 1755.81  4941.9 1756.48  4953.1 1754.03    4959 1753.84  4959.5 1753.34
  4968.7 1753.34  4969.2 1753.84  4996.9 1754.86  5030.3 1754.52  5084.6 1758.78
  5112.9 1759.01  5158.6  1760.7  5272.8 1762.71  5278.3 1762.13  5301.1 1762.93
  5323.9 1762.56  5339.5 1761.34  5375.1 1761.52  5392.4 1763.08  5443.6 1764.44
  5460.9 1765.62    5483 1765.62  5505.1 1767.09  5517.6 1766.71  5530.8 1767.34
#Mann= 3 ,-1 , 0
  4563.8     .05       0    4959     .05       0  4969.2     .05       0
Bank Sta=4959,4969.2
XS Rating Curve= 0 ,0
Exp/Cntr=0.3,0.1

Type RM Length L Ch R = 1 ,4001    ,452,452,452
BEGIN DESCRIPTION:
Elm 02 01 4000.98
END DESCRIPTION:
XS GIS Cut Line= 3
      1603875.32      6824340.77      1604292.03      6824450.15
      1604809.39       6824625.5
#Sta/Elev= 30
    4569 1759.52  4651.4 1758.41  4713.4 1759.23  4796.1    1758  4812.9 1756.14
  4928.8 1753.73  4964.1 1749.84  4964.6 1749.34  4974.3 1749.84  4992.6 1751.49
  4998.8 1753.58    5004 1753.58  5008.5  1755.5  5055.8 1754.44  5071.3 1756.21
  5076.9 1759.29  5087.4 1759.27  5097.4  1757.6  5102.7 1759.21  5119.1 1760.76
  5134.1 1758.41  5140.2 1755.86  5150.8 1754.84  5214.1  1753.4  5385.4 1761.57
  5404.2    1761  5411.6 1762.49  5467.6 1763.34  5479.7 1764.83  5546.1 1765.37
#Mann= 3 ,-1 , 0
    4569     .05       0  4964.1     .05       0  4974.3     .05       0
Bank Sta=4964.1,4974.3
XS Rating Curve= 0 ,0
Exp/Cntr=0.3,0.1

Type RM Length L Ch R = 1 ,3549    ,73,73,73
BEGIN DESCRIPTION:
Elm 02 01 3548.96
END DESCRIPTION:
XS GIS Cut Line= 4
      1603967.07      6824518.16      1604230.25      6824775.94
      1604256.29      6824788.09      1604459.46      6824786.35
#Sta/Elev= 30
  4603.8 1759.87  4672.9 1758.87    4687 1759.43  4694.2 1758.13  4715.3 1757.94
  4722.5 1757.14  4771.9  1756.1  4793.2 1755.22  4807.3 1755.56  4814.3 1755.32
  4821.5 1753.59  4828.5 1753.09  4835.6 1751.04  4842.6 1750.78  4849.8 1749.31
  4856.8 1749.18  4879.8 1746.62  4880.3 1746.12  4889.8 1746.12  4890.3 1746.62
  4913.3 1747.01  4955.8 1746.64  5059.6 1746.81  5069.6 1747.52  5089.6 1750.85
  5109.6 1753.54  5129.6 1757.79  5139.6  1759.2  5169.6 1760.81  5204.1 1761.58
#Mann= 3 ,-1 , 0
  4603.8     .05       0  4879.8     .05       0  4890.3     .05       0
Bank Sta=4879.8,4890.3
XS Rating Curve= 0 ,0
Exp/Cntr=0.3,0.1