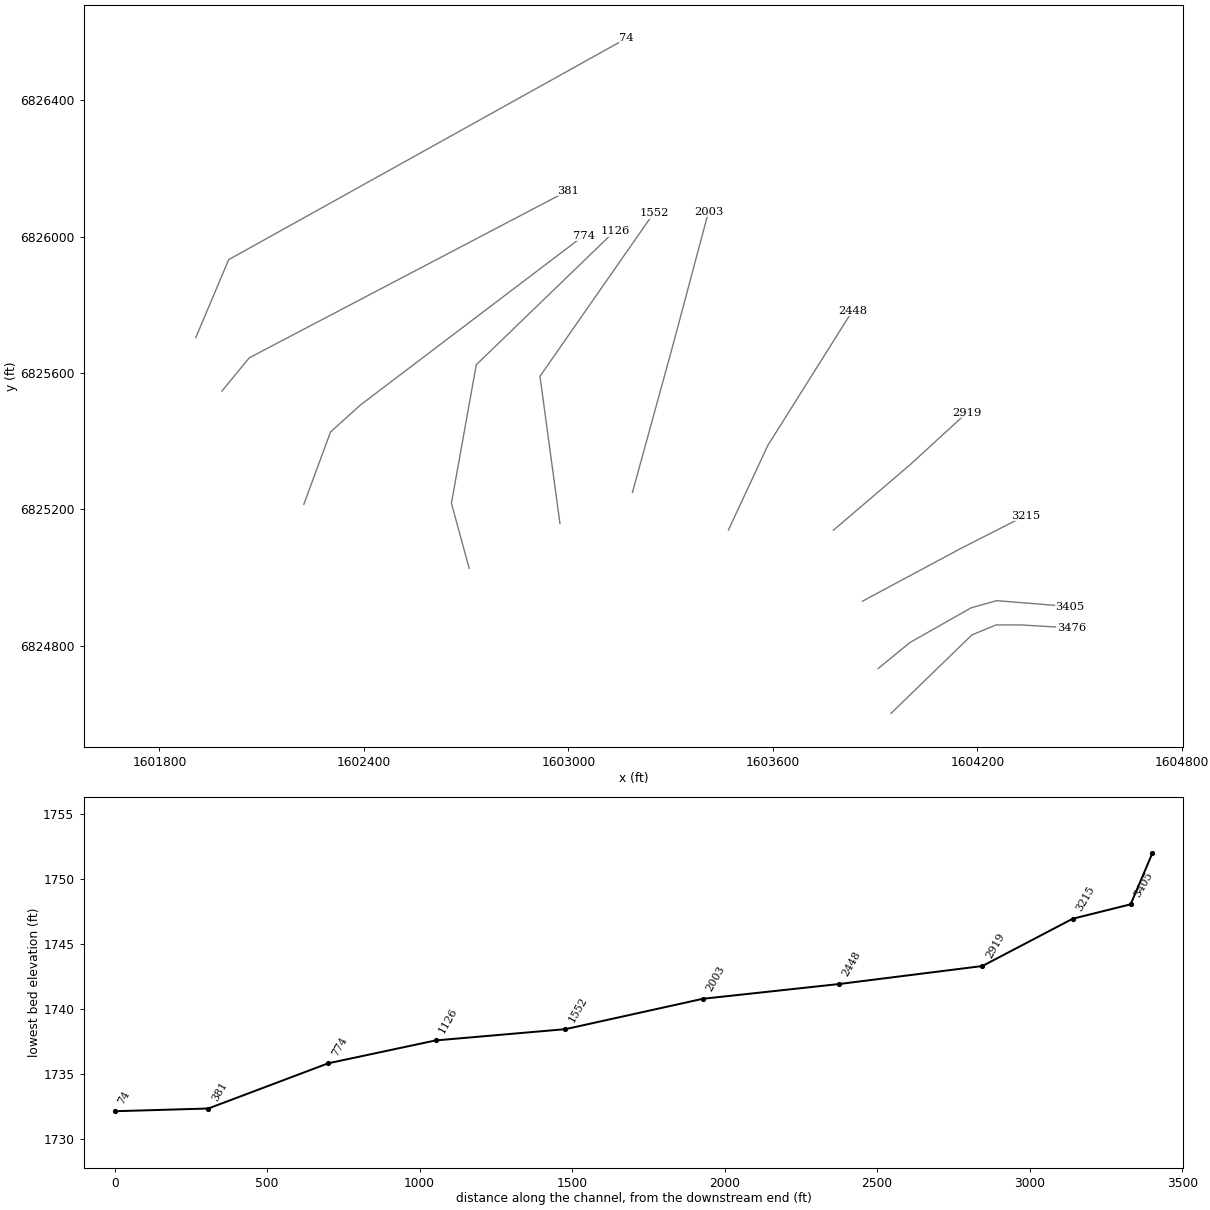
HEC-RAS study Elm 02 01.prj: Elm 02 01 Base Level Engineering

--- Elm 02 01.g01 (geometry) --- (continued)

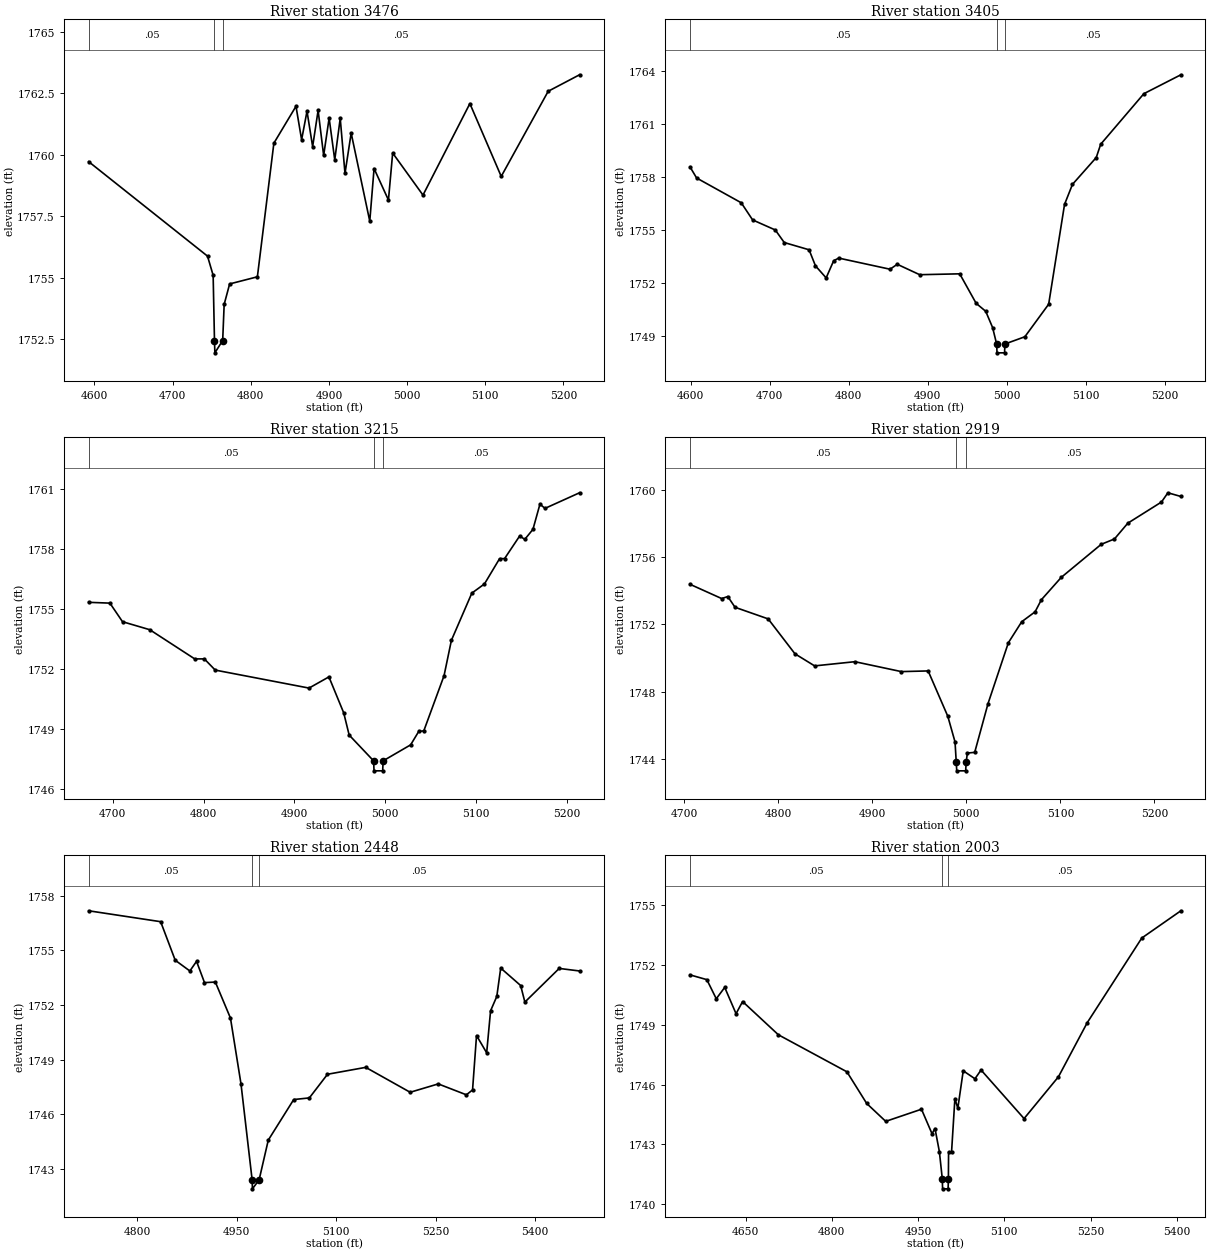
Type RM Length L Ch R = 1 ,3476    ,71,71,71
BEGIN DESCRIPTION:
Elm 02 01 3475.64
END DESCRIPTION:
XS GIS Cut Line= 5
      1603946.27      6824601.52      1604183.37      6824831.49
      1604254.55      6824861.01      1604327.47      6824861.01
      1604475.03      6824852.33
#Sta/Elev= 30
  4592.6 1759.72  4744.7 1755.88  4751.9  1755.1  4753.6 1752.45  4754.1 1751.95
  4764.1 1752.45    4766 1753.92    4773 1754.75  4808.5 1755.04  4829.6 1760.47
  4857.9 1761.97  4865.1 1760.61    4872 1761.77  4879.2 1760.33  4886.2  1761.8
  4893.3 1759.97  4900.3 1761.49  4907.5 1759.79  4914.5 1761.48  4920.6 1759.24
  4928.5 1760.88  4952.3  1757.3  4957.8 1759.44  4976.2 1758.16  4981.6 1760.07
  5020.4 1758.36  5080.4 1762.08  5120.5 1759.12  5180.6 1762.58  5220.7 1763.25
#Mann= 3 ,-1 , 0
  4592.6     .05       0  4753.6     .05       0  4764.1     .05       0
Bank Sta=4753.6,4764.1
XS Rating Curve= 0 ,0
Exp/Cntr=0.3,0.1

Type RM Length L Ch R = 1 ,3405    ,190,190,190
BEGIN DESCRIPTION:
Elm 02 01 3405.2
END DESCRIPTION:
XS GIS Cut Line= 5
      1603908.51      6824733.04      1604001.53      6824809.13
      1604181.64      6824911.35      1604256.29      6824932.19
      1604471.62      6824914.96
#Sta/Elev= 30
  4599.3 1758.55  4607.7 1757.92  4664.1 1756.52  4678.5 1755.55  4707.2 1754.98
  4718.5 1754.27  4749.9 1753.86    4758 1752.95  4771.5 1752.27    4781 1753.24
  4787.4 1753.39  4852.3 1752.76  4861.4 1753.04  4889.8 1752.45  4940.4  1752.5
  4961.2 1750.83  4973.3 1750.38    4982 1749.46  4987.1 1748.53  4987.6 1748.03
  4997.1 1748.03  4997.6 1748.53  5022.8 1748.94  5052.9 1750.78    5073 1756.43
    5083 1757.56  5113.1 1759.08  5118.7 1759.83  5173.3 1762.69  5220.1 1763.76
#Mann= 3 ,-1 , 0
  4599.3     .05       0  4987.1     .05       0  4997.6     .05       0
Bank Sta=4987.1,4997.6
XS Rating Curve= 0 ,0
Exp/Cntr=0.3,0.1

Type RM Length L Ch R = 1 ,3215    ,296,296,296
BEGIN DESCRIPTION:
Elm 02 01 3215.07
END DESCRIPTION:
XS GIS Cut Line= 3
      1603862.17      6824930.44      1604150.39      6825084.97
      1604340.72      6825181.86
#Sta/Elev= 30
  4673.5 1755.35  4696.9 1755.31  4710.8 1754.38  4740.8 1753.98  4790.3 1752.52
  4800.9 1752.52  4812.9 1751.96  4916.2 1751.06  4938.1 1751.62  4954.4 1749.82
  4960.4 1748.71  4987.3 1747.42  4987.8 1746.92  4997.3 1746.92  4997.8 1747.42
  5028.1 1748.22    5037 1748.89  5042.6 1748.92  5064.9 1751.68    5073 1753.45
  5095.5 1755.81  5109.4 1756.27    5126 1757.53  5131.6 1757.54  5148.2 1758.67
  5153.8  1758.5  5162.8    1759  5170.5 1760.26  5176.1 1760.05  5214.1 1760.83
#Mann= 3 ,-1 , 0
  4673.5     .05       0  4987.3     .05       0  4997.8     .05       0
Bank Sta=4987.3,4997.8
XS Rating Curve= 0 ,0
Exp/Cntr=0.3,0.1

Type RM Length L Ch R = 1 ,2919    ,471,471,471
BEGIN DESCRIPTION:
Elm 02 01 2919.16
END DESCRIPTION:
XS GIS Cut Line= 3
      1603777.15      6825138.81      1604002.82      6825331.49
      1604168.79      6825483.64
#Sta/Elev= 30
  4706.2 1754.39  4739.9 1753.54  4746.4 1753.66  4754.1 1753.02  4789.3 1752.33
  4817.8 1750.25  4838.7 1749.53  4881.5 1749.78  4930.9 1749.19  4959.4 1749.23
  4980.3 1746.53    4988    1745  4989.3 1743.78  4989.8 1743.28  4999.3 1743.28
  4999.8 1743.78  5001.1 1744.34  5008.9 1744.38  5023.1 1747.29  5044.7 1750.91
  5058.9 1752.16  5073.1 1752.75  5079.8 1753.47  5100.9  1754.8  5143.4 1756.77
  5157.5 1757.09  5171.7 1758.03  5207.5 1759.29  5214.3 1759.84  5228.1 1759.62
#Mann= 3 ,-1 , 0
  4706.2     .05       0  4989.3     .05       0  4999.8     .05       0
Bank Sta=4989.3,4999.8
XS Rating Curve= 0 ,0
Exp/Cntr=0.3,0.1

Type RM Length L Ch R = 1 ,2448    ,445,445,445
BEGIN DESCRIPTION:
Elm 02 01 2351.663
END DESCRIPTION:
XS GIS Cut Line= 3
      1603469.31      6825139.49      1603584.86       6825387.6
       1603833.7      6825783.26
#Sta/Elev= 30
  4726.3 1757.18    4835 1756.58    4857 1754.46  4879.1 1753.87  4889.2  1754.4
  4901.2 1753.23  4917.6 1753.26  4940.4 1751.28  4956.3 1747.66  4973.1 1742.39
  4973.6 1741.89  4983.7 1742.39  4997.5 1744.57  5035.9  1746.8  5059.5 1746.89
  5086.9 1748.19  5144.6 1748.57  5211.7  1747.2  5254.1 1747.66  5296.6 1747.06
  5305.9 1747.33  5311.9 1750.32  5327.2 1749.37  5333.1 1751.68  5342.5 1752.47
  5348.4 1754.03  5378.5 1753.07  5384.9 1752.16  5436.7 1754.01  5467.4 1753.87
#Mann= 3 ,-1 , 0
  4726.3     .05       0  4973.1     .05       0  4983.7     .05       0
Bank Sta=4973.1,4983.7
XS Rating Curve= 0 ,0
Exp/Cntr=0.3,0.1

Type RM Length L Ch R = 1 ,2003    ,451,451,451
BEGIN DESCRIPTION:
Elm 02 01 2003.46
END DESCRIPTION:
XS GIS Cut Line= 3
      1603187.68      6825249.78      1603307.03      6825683.82
      1603411.02      6826073.75
#Sta/Elev= 30
  4553.3 1751.51  4582.6 1751.27    4599 1750.31  4613.7 1750.88  4633.4 1749.56
  4644.8 1750.17    4707  1748.5  4826.2 1746.64  4860.6 1745.05  4893.7 1744.15
  4955.9 1744.76  4974.2 1743.53  4979.4 1743.79    4987 1742.63  4992.1 1741.26
  4992.6 1740.76  5002.2 1740.76  5002.7 1741.26    5003 1742.61  5008.2 1742.61
    5014 1745.29  5019.1 1744.81  5028.5 1746.69  5048.9 1746.29  5059.5 1746.73
  5134.3 1744.29  5194.1 1746.39  5244.2 1749.11    5339 1753.36    5407 1754.73
#Mann= 3 ,-1 , 0
  4553.3     .05       0  4992.1     .05       0  5002.7     .05       0
Bank Sta=4992.1,5002.7
XS Rating Curve= 0 ,0
Exp/Cntr=0.3,0.1

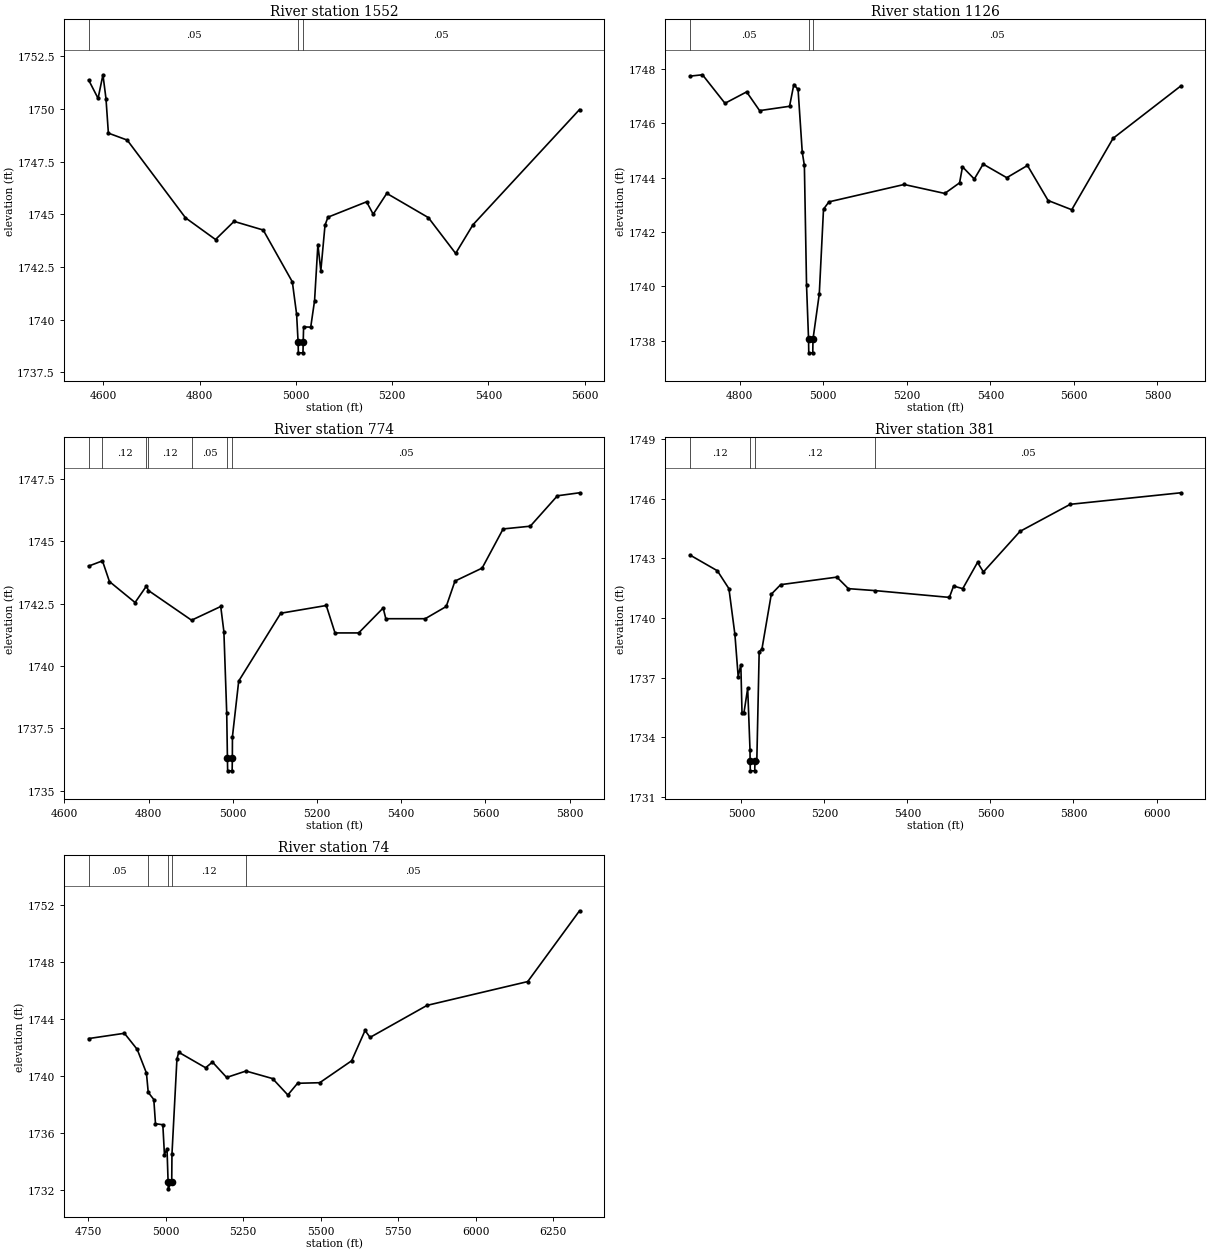
Type RM Length L Ch R = 1 ,1552    ,426,426,426
BEGIN DESCRIPTION:
Elm 02 01 1552.46
END DESCRIPTION:
XS GIS Cut Line= 3
      1602975.01      6825158.61      1602916.41       6825590.5
      1603250.32      6826069.69
#Sta/Elev= 30
  4569.5 1751.37  4589.1  1750.5  4599.2 1751.62  4605.5 1750.49  4610.5 1748.85
  4649.6 1748.52  4770.7 1744.83  4833.1  1743.8  4871.6 1744.66  4932.2 1744.25
  4992.7 1741.79  5001.6 1740.25  5004.7 1738.92  5005.2 1738.42  5014.8 1738.42
  5015.3 1738.92  5016.1 1739.65  5030.9 1739.64  5038.9  1740.9  5045.8 1743.56
  5051.9 1742.32  5060.6 1744.48  5066.7 1744.86    5147 1745.59  5160.7    1745
  5188.9 1745.99  5275.3 1744.84    5332 1743.14    5368  1744.5  5589.4 1749.97
#Mann= 3 ,-1 , 0
  4569.5     .05       0  5004.7     .05       0  5015.3     .05       0
Bank Sta=5004.7,5015.3
XS Rating Curve= 0 ,0
Exp/Cntr=0.3,0.1

Type RM Length L Ch R = 1 ,1126    ,352,352,352
BEGIN DESCRIPTION:
Mapping XS a6ebf7f6
END DESCRIPTION:
XS GIS Cut Line= 4
      1602708.67      6825027.16      1602656.59      6825218.09
      1602729.51      6825624.34      1603135.74      6826016.68
#Sta/Elev= 30
  4680.8 1747.74  4710.7 1747.79  4764.6 1746.74  4816.4 1747.16  4847.5 1746.47
  4919.2 1746.63  4929.4 1747.43  4939.6 1747.25  4949.6 1744.94  4954.7 1744.45
  4959.9 1740.03  4964.7 1738.05  4965.2 1737.55  4974.8 1737.55  4975.3 1738.05
  4990.4 1739.72  5000.5 1742.84  5013.5 1743.11  5193.6 1743.75  5290.8 1743.42
  5326.3 1743.81  5333.3  1744.4  5361.6 1743.95  5382.7  1744.5  5439.3    1744
  5488.9 1744.45  5538.3 1743.16  5594.9 1742.82  5693.9 1745.45  5856.2 1747.38
#Mann= 3 ,-1 , 0
  4680.8     .05       0  4964.7     .07       0  4975.3     .05       0
Bank Sta=4964.7,4975.3
XS Rating Curve= 0 ,0
Exp/Cntr=0.3,0.1

Type RM Length L Ch R = 1 ,774     ,393,393,393
BEGIN DESCRIPTION:
Elm 02 01 774.4
END DESCRIPTION:
XS GIS Cut Line= 4
      1602223.61      6825214.81      1602301.85      6825427.03
      1602389.07      6825505.86      1603044.41       6826002.8
#Sta/Elev= 30
  4657.4    1744  4690.2 1744.21  4706.8 1743.38  4767.7 1742.54  4794.7  1743.2
  4799.5 1743.02  4901.9 1741.83  4971.2 1742.38  4978.7 1741.37  4985.4 1738.12
  4987.1 1736.29  4987.6 1735.79  4998.3 1735.79  4998.8 1736.29    4999 1737.16
  5013.9 1739.39  5113.8 1742.11  5221.9 1742.42  5242.7 1741.32  5298.9 1741.32
  5357.1 1742.32  5363.4 1741.89    5457 1741.89  5506.9 1742.38  5527.7  1743.4
  5592.2 1743.92  5642.1 1745.49  5706.6  1745.6  5771.1 1746.82  5823.6 1746.94
#Mann= 7 ,-1 , 0
  4657.4     .05       0  4690.2     .12       0  4794.7     .05       0
  4799.5     .12       0  4901.9     .05       0  4987.1     .05       0
  4998.8     .05       0
Bank Sta=4987.1,4998.8
XS Rating Curve= 0 ,0
Exp/Cntr=0.3,0.1

Type RM Length L Ch R = 1 ,381     ,307,307,307
BEGIN DESCRIPTION:
Elm 02 01 380.75
END DESCRIPTION:
XS GIS Cut Line= 3
      1601983.23      6825547.07      1602063.54      6825644.75
      1602998.89      6826135.21
#Sta/Elev= 30
  4876.1 1743.16    4942 1742.37  4969.9 1741.47  4984.3 1739.17  4992.2 1737.05
  4998.6 1737.65  5001.4 1735.24  5006.2 1735.24  5015.1 1736.46  5020.7 1733.36
  5020.9 1732.81  5021.4 1732.31  5032.1 1732.31  5032.6 1732.81  5037.1 1732.81
  5042.8 1738.31  5049.4 1738.43    5072 1741.19  5094.5 1741.67    5230 1742.05
  5257.7 1741.47  5322.9 1741.37    5501 1741.03  5511.1  1741.6  5533.2 1741.47
  5568.8 1742.79    5583 1742.31  5671.2 1744.35  5792.2 1745.71  6058.7 1746.29
#Mann= 4 ,-1 , 0
  4876.1     .12       0  5020.9     .07       0  5032.6     .12       0
  5322.9     .05       0
Bank Sta=5020.9,5032.6
XS Rating Curve= 0 ,0
Exp/Cntr=0.3,0.1

Type RM Length L Ch R = 1 ,74      ,0,0,0
BEGIN DESCRIPTION:
Elm 02 01 1888.607
END DESCRIPTION:
XS GIS Cut Line= 3
      1601906.44      6825703.66        1602003.      6825932.63
       1603170.2      6826582.04
#Sta/Elev= 30
  4751.5 1742.65  4866.9 1743.02  4908.2 1741.89    4938 1740.23  4943.8 1738.87
  4961.8 1738.37  4967.2 1736.67  4990.9  1736.6  4996.1 1734.51  5004.4 1734.91
  5007.9  1732.6  5008.4  1732.1  5019.6  1732.6  5020.4 1734.54  5036.4 1741.21
  5042.1 1741.69    5129  1740.6  5151.1    1741  5196.8 1739.92  5259.2 1740.37
  5345.1 1739.84  5394.3 1738.69  5425.7 1739.51  5497.2 1739.55  5600.2 1741.09
  5643.6 1743.22  5659.6 1742.73  5843.7 1744.98  6168.5 1746.65  6335.7 1751.62
#Mann= 5 ,-1 , 0
  4751.5     .05       0  4943.8     .12       0  5007.9     .07       0
  5019.6     .12       0  5259.2     .05       0
Bank Sta=5007.9,5019.6
XS Rating Curve= 0 ,0
Exp/Cntr=0.3,0.1

Chan Stop Cuts=-1
Use User Specified Reach Order=0
Composite Channel Slope=5