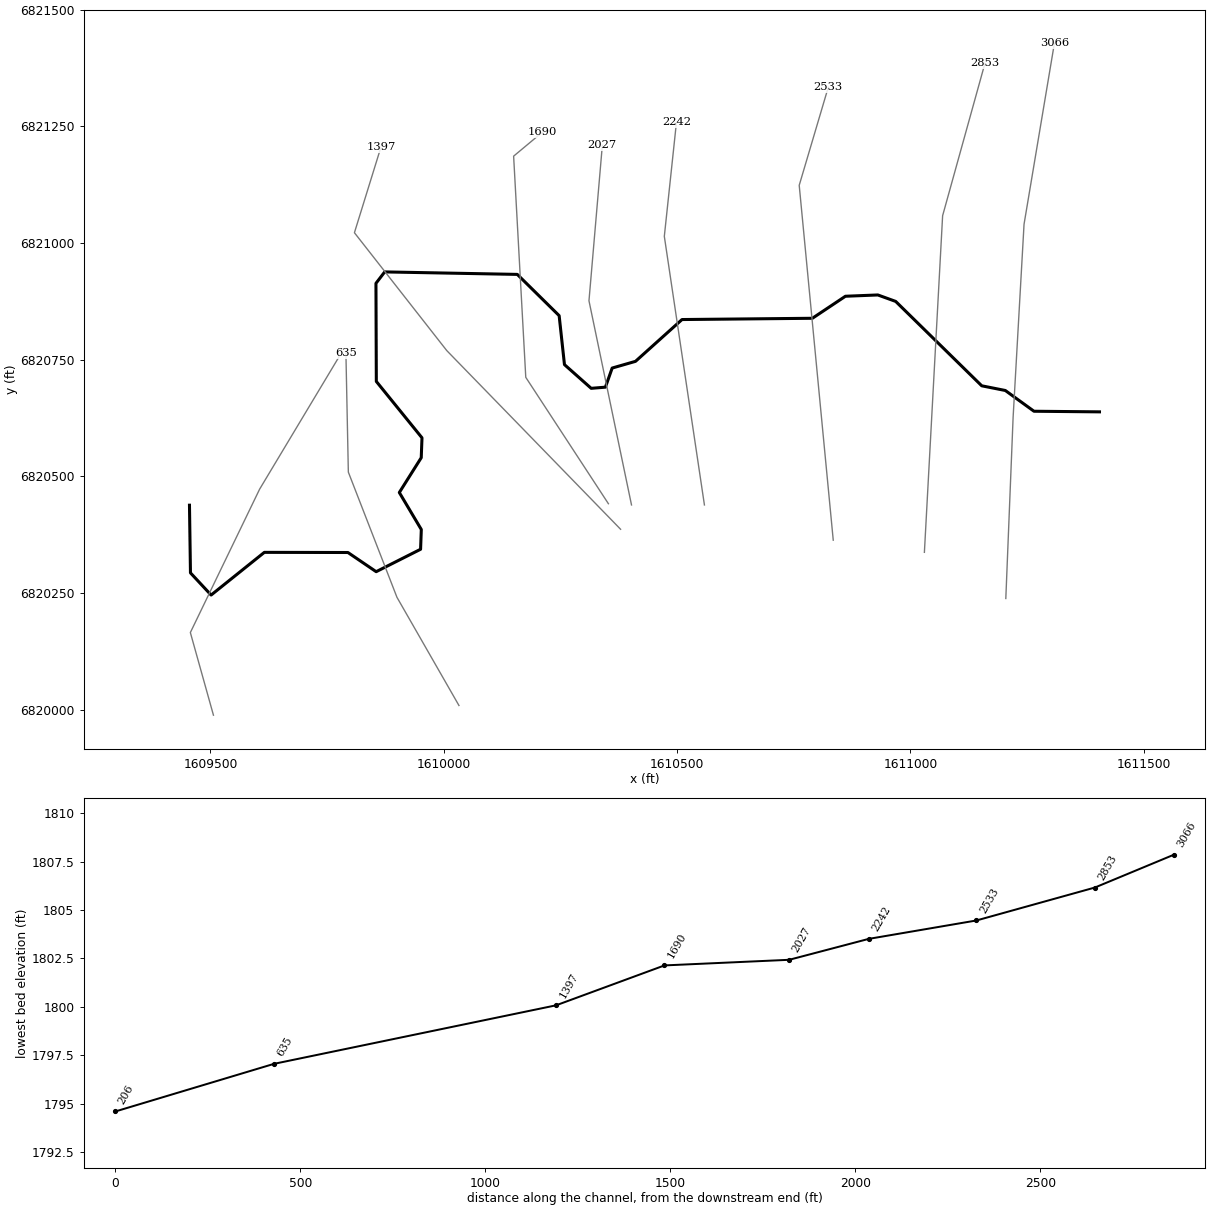
--- Elm 02 02.prj (project) ---

Proj Title=Elm 02 02 Base Level Engineering
Current Plan=p01
Default Exp/Contr=0.3,0.1
English Units
Geom File=g01
Flow File=f01
Plan File=p01
BEGIN DESCRIPTION:
Elm 02 02
END DESCRIPTION:

--- Elm 02 02.p01 (plan) ---

Plan Title=Multiple Run
Short Identifier=Multiple
Geom File=g01
Flow File=f01
Subcritical Flow
K Sum by GR= 0
Std Step Tol= 0.01
Critical Tol= 0.01
Num of Std Step Trials= 20
Max Error Tol= 0.3
Flow Tol Ratio= 0.001
Split Flow NTrial= 30
Split Flow Tol= 0.02
Split Flow Ratio= 0.02
Log Output Level= 0
Friction Slope Method= 1
Unsteady Friction Slope Method= 2
Unsteady Bridges Friction Slope Method= 1
Parabolic Critical Depth
Global Vel Dist=  1 , 1 , 1
Global Log Level= 0
CheckData=True
Encroach Param= -1, 0, 0, 0
BEGIN DESCRIPTION:
Multiple Run
END DESCRIPTION:

--- Elm 02 02.f01 (steady flow) ---

Flow Title=Multiple
Number of Profiles=7
Profile Names=10-year,25-year,50-year,1pct_min,100-year,1pct_plu,500-year
River Rch & RM= Elm 02 02,Reach-1,3066
     191     259     314     236     379     521     558
Boundary for River Rch & Prof#=Elm 02 02,Reach-1,1
Up Type=0
Dn Type=3
Dn Slope=0.001
Boundary for River Rch & Prof#=Elm 02 02,Reach-1,2
Up Type=0
Dn Type=3
Dn Slope=0.001
Boundary for River Rch & Prof#=Elm 02 02,Reach-1,3
Up Type=0
Dn Type=3
Dn Slope=0.001
Boundary for River Rch & Prof#=Elm 02 02,Reach-1,4
Up Type=0
Dn Type=3
Dn Slope=0.001
Boundary for River Rch & Prof#=Elm 02 02,Reach-1,5
Up Type=0
Dn Type=3
Dn Slope=0.001
Boundary for River Rch & Prof#=Elm 02 02,Reach-1,6
Up Type=0
Dn Type=3
Dn Slope=0.001
Boundary for River Rch & Prof#=Elm 02 02,Reach-1,7
Up Type=0
Dn Type=3
Dn Slope=0.001

--- Elm 02 02.g01 (geometry) ---

Geom Title=Existing Conditions

River Reach=Elm 02 02,Reach-1
Reach XY= 30
      1611405.00      6820638.00      1611264.63      6820639.31
      1611203.25      6820683.78      1611152.70      6820693.83
      1610968.30      6820874.66      1610930.04      6820888.50
      1610860.57      6820885.72      1610789.78      6820838.52
      1610510.45      6820835.82      1610410.76      6820746.24
      1610360.77      6820731.86      1610346.32      6820690.90
      1610315.81      6820688.43      1610258.55      6820739.21
      1610247.14      6820844.19      1610157.47      6820932.55
      1609873.31      6820937.88      1609854.58      6820913.42
      1609855.39      6820703.16      1609953.25      6820582.37
      1609951.63      6820539.74      1609904.65      6820465.19
      1609951.78      6820385.90      1609950.22      6820343.55
      1609855.05      6820295.52      1609794.56      6820336.62
      1609615.43      6820336.94      1609501.38      6820245.47
      1609457.12      6820292.99      1609455.00      6820438.00

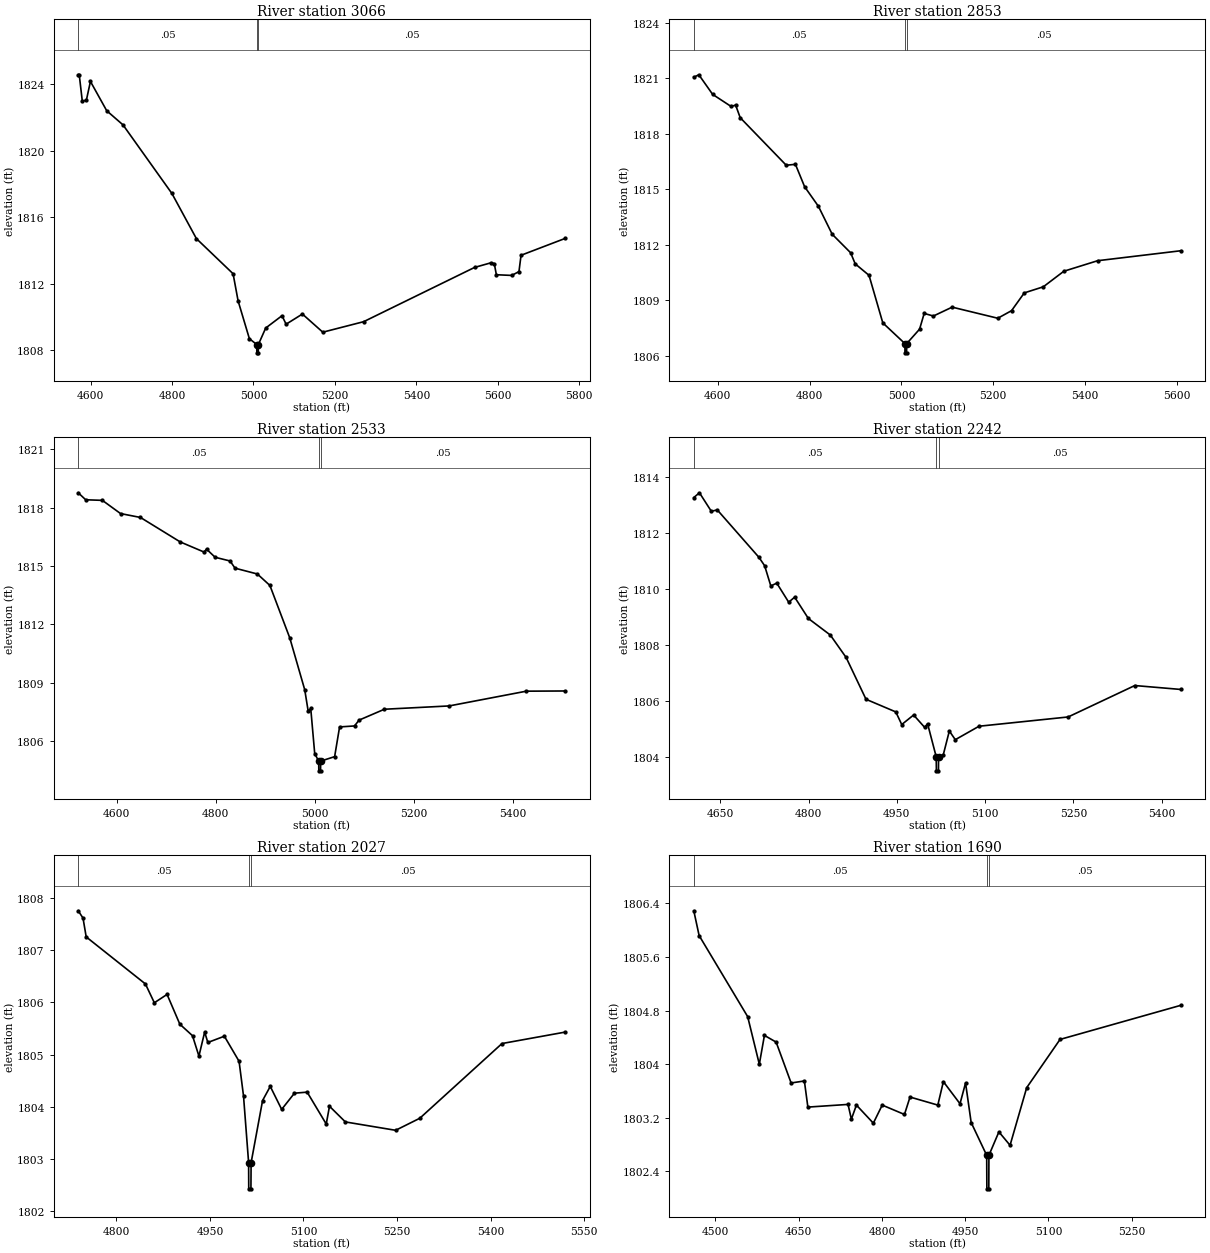
Type RM Length L Ch R = 1,3066,213,213,213
BEGIN DESCRIPTION:
Elm 02 02 2.0
END DESCRIPTION:
XS GIS Cut Line= 4
      1611204.29      6820238.05      1611219.91      6820626.03
      1611243.35      6821040.10      1611308.46      6821428.14
#Sta/Elev= 30
  4569.6 1824.55  4572.1 1824.55  4579.6 1822.97  4589.6 1823.02  4599.6 1824.15
  4639.6 1822.39  4679.6 1821.54  4799.7 1817.42  4859.8 1814.71  4949.9 1812.60
  4962.2 1810.97  4989.9 1808.70  5008.0 1808.35  5008.2 1807.85  5011.7 1807.85
  5012.0 1808.35  5030.0 1809.34  5070.0 1810.08  5080.1 1809.57  5120.1 1810.18
  5170.2 1809.09  5270.4 1809.72  5542.9 1812.98  5583.4 1813.26  5591.3 1813.21
  5596.4 1812.54  5634.1 1812.50  5651.9 1812.73  5657.0 1813.71  5766.1 1814.73
#Mann=3,-1,0
  4569.6    0.05       0  5008.0    0.05       0  5012.0    0.05       0
Bank Sta=5008,5012
Exp/Cntr=0.3,0.1

Type RM Length L Ch R = 1,2853,320,320,320
BEGIN DESCRIPTION:
Mapping XS 64d1a06d
END DESCRIPTION:
XS GIS Cut Line= 3
      1611029.81      6820337.00      1611068.87      6821058.33
      1611159.53      6821384.69
#Sta/Elev= 30
  4547.9 1821.06  4558.9 1821.19  4589.0 1820.13  4629.0 1819.48  4639.0 1819.55
  4649.0 1818.87  4749.2 1816.30  4769.2 1816.35  4789.2 1815.14  4819.3 1814.08
  4849.3 1812.57  4889.4 1811.57  4899.4 1810.97  4929.5 1810.35  4959.5 1807.78
  5007.6 1806.66  5007.8 1806.16  5011.3 1806.16  5011.6 1806.66  5039.6 1807.44
  5049.6 1808.29  5069.7 1808.15  5110.5 1808.63  5209.9 1808.03  5239.9 1808.44
  5267.6 1809.40  5309.1 1809.73  5353.7 1810.57  5427.4 1811.14  5609.0 1811.68
#Mann=3,-1,0
  4547.9    0.05       0  5007.6    0.05       0  5011.6    0.05       0
Bank Sta=5007.6,5011.6
Exp/Cntr=0.3,0.1

Type RM Length L Ch R = 1,2533,291,291,291
BEGIN DESCRIPTION:
Mapping XS 6ad8133b
END DESCRIPTION:
XS GIS Cut Line= 3
      1610834.50      6820363.00      1610761.58      6821123.43
      1610823.88      6821333.68
#Sta/Elev= 30
  4522.3 1818.77  4537.4 1818.41  4571.0 1818.38  4607.7 1817.70  4647.9 1817.50
  4728.2 1816.24  4776.2 1815.72  4781.2 1815.87  4798.6 1815.45  4828.7 1815.26
  4838.7 1814.89  4883.8 1814.59  4909.1 1814.00  4949.2 1811.30  4979.4 1808.63
  4986.4 1807.52  4991.5 1807.67  4999.5 1805.35  5007.5 1804.96  5007.8 1804.46
  5011.3 1804.46  5011.5 1804.96  5039.7 1805.19  5049.7 1806.72  5079.8 1806.77
  5089.0 1807.07  5140.1 1807.63  5270.7 1807.80  5426.6 1808.56  5505.5 1808.57
#Mann=3,-1,0
  4522.3    0.05       0  5007.5    0.05       0  5011.5    0.05       0
Bank Sta=5007.5,5011.5
Exp/Cntr=0.3,0.1

Type RM Length L Ch R = 1,2242,215,215,215
BEGIN DESCRIPTION:
Mapping XS 0ef08fdf
END DESCRIPTION:
XS GIS Cut Line= 3
      1610558.46      6820438.51      1610472.52      6821014.06
      1610498.56      6821258.85
#Sta/Elev= 30
  4605.0 1813.25  4614.6 1813.42  4634.8 1812.76  4644.9 1812.81  4715.7 1811.12
  4725.4 1810.82  4735.9 1810.10  4746.0 1810.20  4766.3 1809.52  4776.4 1809.70
  4799.7 1808.94  4837.0 1808.35  4863.9 1807.55  4897.7 1806.06  4948.3 1805.61
  4958.4 1805.16  4978.6 1805.50  4997.3 1805.06  5002.3 1805.19  5017.0 1804.01
  5017.3 1803.51  5020.8 1803.51  5021.0 1804.01  5029.1 1804.09  5039.3 1804.93
  5049.4 1804.62  5089.8 1805.10  5241.2 1805.43  5354.5 1806.55  5433.1 1806.41
#Mann=3,-1,0
  4605.0    0.05       0  5017.0    0.05       0  5021.0    0.05       0
Bank Sta=5017,5021
Exp/Cntr=0.3,0.1

Type RM Length L Ch R = 1,2027,337,337,337
BEGIN DESCRIPTION:
Mapping XS ccea7836
END DESCRIPTION:
XS GIS Cut Line= 3
      1610402.21      6820438.51      1610311.06      6820876.03
      1610339.71      6821209.39
#Sta/Elev= 30
  4738.7 1807.75  4746.4 1807.61  4751.5 1807.25  4846.5 1806.35  4860.8 1805.99
  4881.2 1806.15  4901.7 1805.58  4922.0 1805.36  4932.3 1804.97  4941.5 1805.43
  4946.6 1805.23  4973.1 1805.35  4996.7 1804.87  5003.8 1804.21  5012.0 1802.93
  5012.2 1802.43  5015.7 1802.43  5016.0 1802.93  5034.4 1804.12  5046.7 1804.39
  5065.0 1803.95  5085.5 1804.26  5105.9 1804.28  5136.5 1803.67  5141.7 1804.01
  5167.2 1803.71  5247.8 1803.55  5286.5 1803.78  5418.4 1805.21  5520.2 1805.43
#Mann=3,-1,0
  4738.7    0.05       0  5012.0    0.05       0  5016.0    0.05       0
Bank Sta=5012,5016
Exp/Cntr=0.3,0.1

Type RM Length L Ch R = 1,1690,293,293,293
BEGIN DESCRIPTION:
Mapping XS fe69d573
END DESCRIPTION:
XS GIS Cut Line= 4
      1610352.71      6820441.16      1610175.64      6820711.97
      1610149.60      6821185.93      1610211.03      6821237.12
#Sta/Elev= 30
  4460.9 1806.29  4470.5 1805.92  4558.0 1804.71  4579.0 1804.00  4588.2 1804.43
  4609.3 1804.33  4636.3 1803.72  4660.2 1803.75  4666.5 1803.36  4738.9 1803.40
  4744.9 1803.18  4754.0 1803.39  4784.5 1803.12  4800.5 1803.39  4840.6 1803.25
  4850.6 1803.51  4900.7 1803.39  4910.7 1803.74  4940.7 1803.41  4950.7 1803.72
  4960.8 1803.13  4988.8 1802.64  4989.1 1802.14  4992.6 1802.14  4992.8 1802.64
  5010.8 1802.99  5030.9 1802.79  5060.9 1803.65  5121.0 1804.37  5339.1 1804.88
#Mann=3,-1,0
  4460.9    0.05       0  4988.8    0.05       0  4992.8    0.05       0
Bank Sta=4988.8,4992.8
Exp/Cntr=0.3,0.1

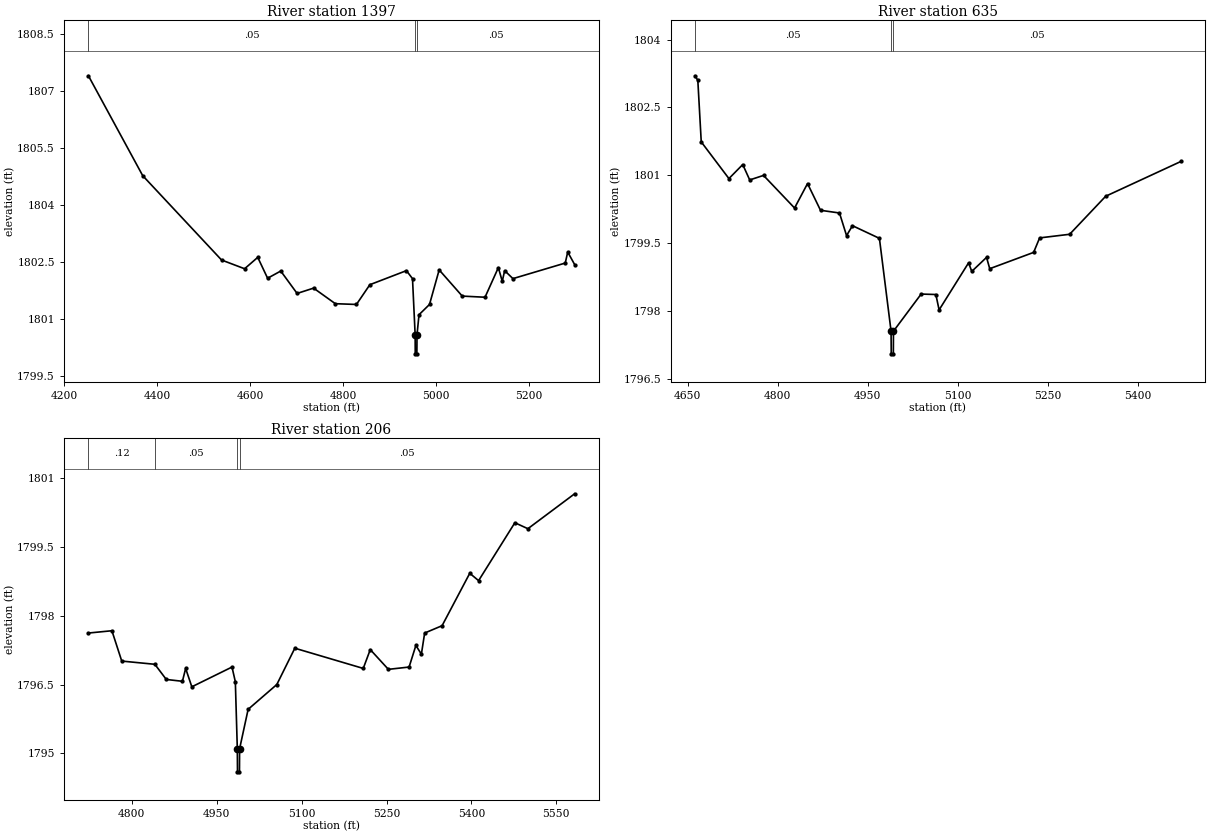
Type RM Length L Ch R = 1,1397,762,762,762
BEGIN DESCRIPTION:
Mapping XS 7e301a5a
END DESCRIPTION:
XS GIS Cut Line= 4
      1610378.79      6820386.43      1610006.37      6820769.26
      1609808.45      6821021.87      1609865.16      6821204.88
#Sta/Elev= 30
  4251.7 1807.40  4368.6 1804.77  4538.3 1802.55  4587.9 1802.32  4616.2 1802.62
  4637.4 1802.07  4665.7 1802.26  4700.9 1801.67  4736.4 1801.81  4783.2 1801.40
  4828.6 1801.38  4857.5 1801.90  4936.2 1802.27  4949.3 1802.06  4955.0 1800.58
  4955.2 1800.08  4958.7 1800.08  4959.0 1800.58  4963.3 1801.11  4985.9 1801.38
  5006.7 1802.29  5056.4 1801.60  5105.4 1801.57  5134.1 1802.35  5142.5 1801.99
  5147.7 1802.27  5165.5 1802.06  5278.1 1802.47  5283.4 1802.76  5298.3 1802.43
#Mann=3,-1,0
  4251.7    0.05       0  4955.0    0.05       0  4959.0    0.05       0
Bank Sta=4955,4959
Exp/Cntr=0.3,0.1

Type RM Length L Ch R = 1,635,429,429,429
BEGIN DESCRIPTION:
Mapping XS 1a3781ec
END DESCRIPTION:
XS GIS Cut Line= 4
      1610032.44      6820008.81      1609899.60      6820240.62
      1609795.43      6820508.85      1609790.23      6820763.58
#Sta/Elev= 30
  4662.0 1803.20  4666.9 1803.10  4672.6 1801.74  4718.7 1800.93  4741.7 1801.24
  4753.3 1800.90  4776.3 1801.00  4828.0 1800.28  4849.6 1800.82  4871.2 1800.23
  4902.8 1800.17  4914.6 1799.67  4924.4 1799.89  4969.3 1799.61  4988.7 1797.56
  4989.0 1797.06  4992.5 1797.06  4992.7 1797.56  5038.8 1798.38  5063.3 1798.37
  5068.7 1798.03  5117.8 1799.07  5123.1 1798.88  5147.7 1799.19  5153.0 1798.94
  5226.1 1799.30  5236.1 1799.62  5286.1 1799.70  5346.1 1800.54  5471.7 1801.31
#Mann=3,-1,0
  4662.0    0.05       0  4988.7    0.05       0  4992.7    0.05       0
Bank Sta=4988.7,4992.7
Exp/Cntr=0.3,0.1

Type RM Length L Ch R = 1,206,0,0,0
BEGIN DESCRIPTION:
Elm 02 02 1.0
END DESCRIPTION:
XS GIS Cut Line= 4
      1609506.36      6819988.06      1609456.89      6820165.10
      1609605.33      6820472.39      1609777.18      6820758.81
#Sta/Elev= 30
  4723.3 1797.62  4764.8 1797.67  4782.2 1797.01  4840.7 1796.94  4860.9 1796.61
  4889.4 1796.57  4895.1 1796.85  4906.0 1796.45  4977.0 1796.88  4982.9 1796.56
  4986.4 1795.10  4986.7 1794.60  4990.2 1794.60  4990.4 1795.10  5005.5 1795.96
  5056.2 1796.50  5088.0 1797.29  5208.9 1796.85  5221.3 1797.26  5253.3 1796.83
  5289.9 1796.88  5301.9 1797.35  5311.6 1797.16  5317.4 1797.62  5348.2 1797.78
  5397.1 1798.92  5412.7 1798.76  5476.8 1800.02  5499.8 1799.89  5582.4 1800.65
#Mann=4,-1,0
  4723.3    0.12       0  4840.7    0.05       0  4986.4    0.05       0
  4990.4    0.05       0
Bank Sta=4986.4,4990.4
Exp/Cntr=0.3,0.1

Chan Stop Cuts=-1