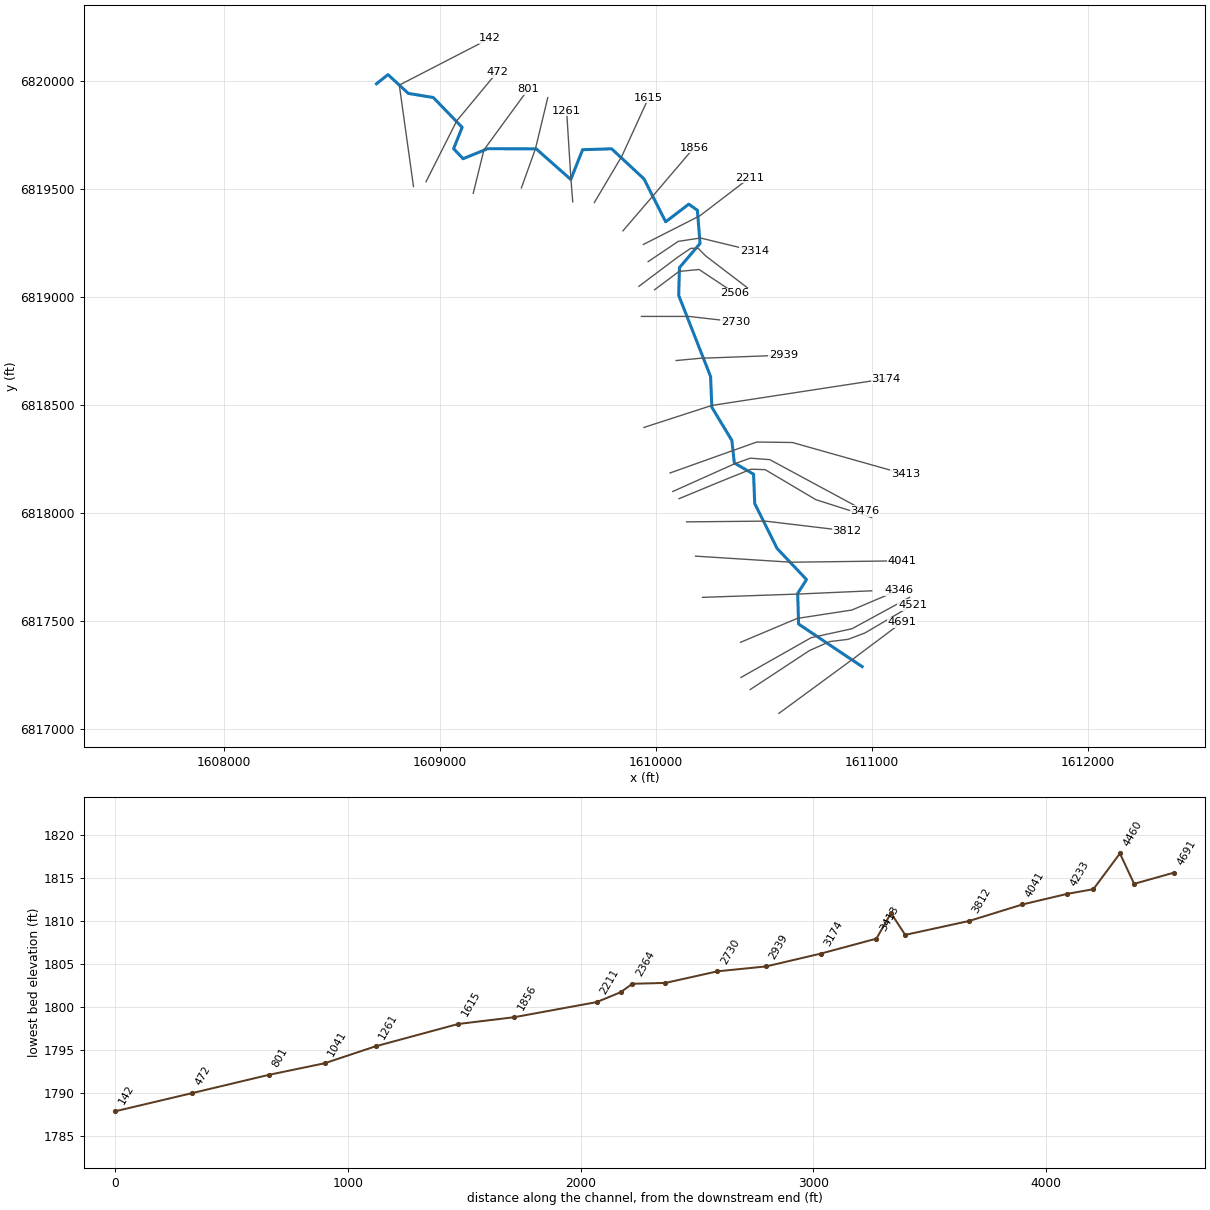
--- Elm 02 03.prj (project) ---

Proj Title=Elm 02 03 Base Level Engineering
Current Plan=p01
Default Exp/Contr=0.3,0.1
English Units
Geom File=g01
Flow File=f01
Plan File=p01
BEGIN DESCRIPTION:
Elm 02 03
END DESCRIPTION:

--- Elm 02 03.p01 (plan) ---

Plan Title=Multiple Run
Short Identifier=Multiple
Geom File=g01
Flow File=f01
Subcritical Flow
K Sum by GR= 0
Std Step Tol= 0.01
Critical Tol= 0.01
Num of Std Step Trials= 20
Max Error Tol= 0.3
Flow Tol Ratio= 0.001
Split Flow NTrial= 30
Split Flow Tol= 0.02
Split Flow Ratio= 0.02
Log Output Level= 0
Friction Slope Method= 1
Unsteady Friction Slope Method= 2
Unsteady Bridges Friction Slope Method= 1
Parabolic Critical Depth
Global Vel Dist=  1 , 1 , 1
Global Log Level= 0
CheckData=True
Encroach Param= -1, 0, 0, 0
BEGIN DESCRIPTION:
Multiple Run
END DESCRIPTION:

--- Elm 02 03.f01 (steady flow) ---

Flow Title=Multiple
Number of Profiles=7
Profile Names=10-year,25-year,50-year,1pct_min,100-year,1pct_plu,500-year
River Rch & RM= Elm 02 03,Reach-1,4691
     184     249     301     226     363     499     533
Boundary for River Rch & Prof#=Elm 02 03,Reach-1,1
Up Type=0
Dn Type=3
Dn Slope=0.001
Boundary for River Rch & Prof#=Elm 02 03,Reach-1,2
Up Type=0
Dn Type=3
Dn Slope=0.001
Boundary for River Rch & Prof#=Elm 02 03,Reach-1,3
Up Type=0
Dn Type=3
Dn Slope=0.001
Boundary for River Rch & Prof#=Elm 02 03,Reach-1,4
Up Type=0
Dn Type=3
Dn Slope=0.001
Boundary for River Rch & Prof#=Elm 02 03,Reach-1,5
Up Type=0
Dn Type=3
Dn Slope=0.001
Boundary for River Rch & Prof#=Elm 02 03,Reach-1,6
Up Type=0
Dn Type=3
Dn Slope=0.001
Boundary for River Rch & Prof#=Elm 02 03,Reach-1,7
Up Type=0
Dn Type=3
Dn Slope=0.001

--- Elm 02 03.g01 (geometry) ---

Geom Title=Existing Conditions

River Reach=Elm 02 03,Reach-1
Reach XY= 30
      1610955.00      6817288.00      1610660.45      6817485.54
      1610656.38      6817627.56      1610697.21      6817691.42
      1610560.83      6817835.70      1610457.25      6818043.94
      1610451.89      6818179.68      1610362.79      6818231.57
      1610351.17      6818336.41      1610258.76      6818489.56
      1610252.73      6818632.06      1610105.05      6819008.04
      1610108.54      6819136.53      1610203.96      6819248.44
      1610191.63      6819402.16      1610151.87      6819430.47
      1610044.68      6819348.83      1609944.24      6819547.68
      1609794.55      6819686.97      1609660.08      6819682.97
      1609605.24      6819544.97      1609444.57      6819686.95
      1609220.21      6819687.46      1609106.16      6819641.12
      1609062.26      6819687.64      1609101.84      6819786.35
      1608968.30      6819924.60      1608852.57      6819943.55
      1608758.33      6820030.73      1608705.00      6819988.00

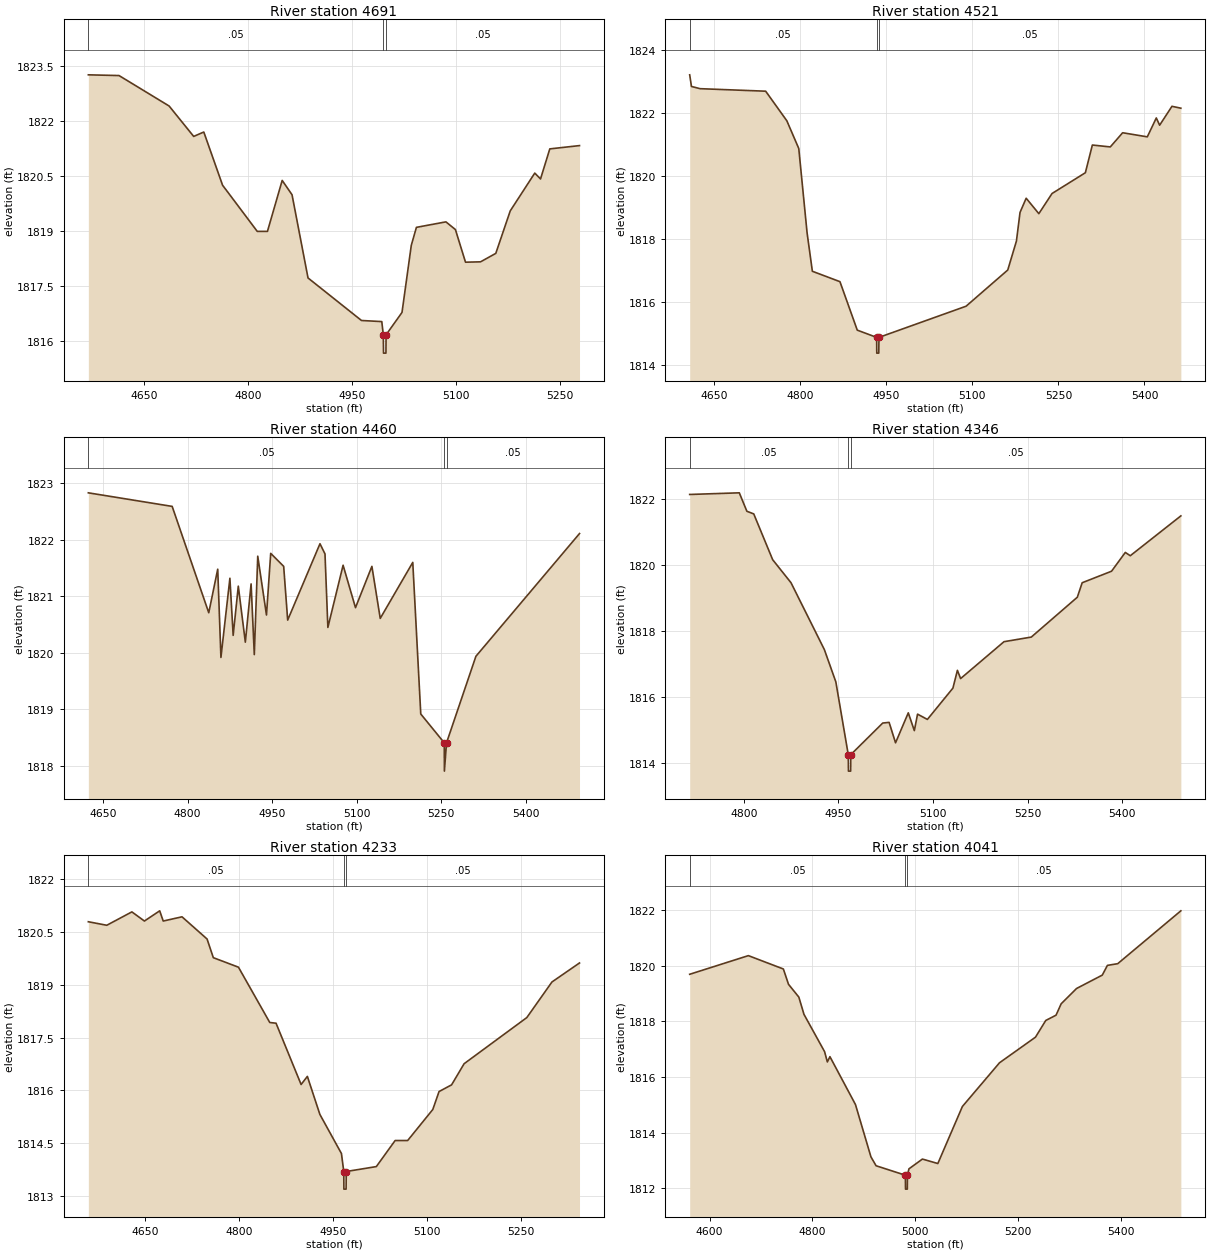
Type RM Length L Ch R = 1,4691,170,170,170
BEGIN DESCRIPTION:
Elm 02 03 4690.81
END DESCRIPTION:
XS GIS Cut Line= 3
      1610569.31      6817071.63      1610916.78      6817326.62
      1611139.34      6817493.54
#Sta/Elev= 30
  4569.0 1823.25  4613.3 1823.23  4685.6 1822.40  4721.1 1821.57  4735.7 1821.69
  4762.8 1820.24  4812.9 1818.98  4827.6 1818.98  4848.9 1820.37  4863.1 1819.98
  4886.2 1817.71  4963.4 1816.55  4992.7 1816.52  4994.9 1816.16  4995.2 1815.66
  4998.7 1815.66  4998.9 1816.16  5021.9 1816.77  5035.3 1818.60  5042.7 1819.09
  5085.3 1819.24  5099.0 1819.03  5113.6 1818.14  5135.3 1818.15  5157.3 1818.38
  5178.2 1819.54  5213.6 1820.57  5221.9 1820.41  5235.3 1821.23  5278.2 1821.32
#Mann=3,-1,0
  4569.0    0.05       0  4994.9    0.05       0  4998.9    0.05       0
Bank Sta=4994.9,4998.9
Exp/Cntr=0.3,0.1

Type RM Length L Ch R = 1,4521,61,61,61
BEGIN DESCRIPTION:
Mapping XS 425d88c1
END DESCRIPTION:
XS GIS Cut Line= 6
      1610436.38      6817181.97      1610710.65      6817362.51
      1610804.40      6817404.17      1610889.47      6817414.59
      1610967.60      6817444.10      1611188.67      6817573.64
#Sta/Elev= 30
  4607.1 1823.21  4610.2 1822.84  4625.3 1822.77  4739.6 1822.69  4776.5 1821.75
  4797.3 1820.87  4811.8 1818.19  4821.0 1816.97  4869.1 1816.64  4899.3 1815.10
  4933.1 1814.87  4933.3 1814.37  4936.8 1814.37  4937.1 1814.87  5089.0 1815.86
  5161.7 1817.01  5176.8 1817.93  5183.1 1818.84  5193.8 1819.29  5215.9 1818.80
  5238.9 1819.44  5297.0 1820.10  5309.2 1820.98  5340.5 1820.92  5362.0 1821.37
  5405.0 1821.24  5420.7 1821.84  5426.5 1821.61  5448.0 1822.21  5463.5 1822.15
#Mann=3,-1,0
  4607.1    0.05       0  4933.1    0.05       0  4937.1    0.05       0
Bank Sta=4933.1,4937.1
Exp/Cntr=0.3,0.1

Type RM Length L Ch R = 1,4460,114,114,114
BEGIN DESCRIPTION:
Elm 02 03 4459.79
END DESCRIPTION:
XS GIS Cut Line= 4
      1610393.56      6817238.03      1610719.04      6817422.46
      1610907.85      6817463.70      1611174.76      6817609.09
#Sta/Elev= 30
  4624.1 1822.83  4772.8 1822.59  4837.7 1820.71  4853.6 1821.48  4859.3 1819.92
  4875.2 1821.32  4881.0 1820.31  4890.1 1821.18  4902.6 1820.19  4912.8 1821.22
  4918.5 1819.97  4924.6 1821.71  4940.1 1820.67  4947.6 1821.76  4970.6 1821.53
  4977.7 1820.58  5035.0 1821.93  5043.9 1821.75  5049.0 1820.45  5076.0 1821.55
  5098.0 1820.80  5127.1 1821.53  5141.9 1820.61  5199.6 1821.60  5213.8 1818.92
  5255.5 1818.41  5255.7 1817.91  5259.5 1818.41  5311.6 1819.94  5495.4 1822.11
#Mann=3,-1,0
  4624.1    0.05       0  5255.5    0.05       0  5259.5    0.05       0
Bank Sta=5255.5,5259.5
Exp/Cntr=0.3,0.1

Type RM Length L Ch R = 1,4346,113,113,113
BEGIN DESCRIPTION:
Elm 02 03 4345.82
END DESCRIPTION:
XS GIS Cut Line= 4
      1610391.40      6817400.78      1610653.94      6817511.44
      1610907.85      6817550.50      1611126.09      6817643.42
#Sta/Elev= 30
  4714.0 1822.15  4792.7 1822.20  4804.7 1821.64  4815.6 1821.56  4845.6 1820.17
  4874.7 1819.47  4927.6 1817.44  4945.8 1816.46  4965.5 1814.25  4965.8 1813.75
  4969.3 1813.75  4969.5 1814.25  5020.2 1815.21  5030.3 1815.23  5040.5 1814.61
  5060.7 1815.52  5070.3 1814.98  5075.4 1815.48  5091.0 1815.32  5131.5 1816.27
  5138.6 1816.81  5143.7 1816.56  5212.5 1817.68  5255.8 1817.82  5328.8 1819.03
  5336.5 1819.47  5383.1 1819.82  5404.9 1820.39  5412.8 1820.29  5493.0 1821.50
#Mann=3,-1,0
  4714.0    0.05       0  4965.5    0.05       0  4969.5    0.05       0
Bank Sta=4965.5,4969.5
Exp/Cntr=0.3,0.1

Type RM Length L Ch R = 1,4233,192,192,192
BEGIN DESCRIPTION:
Elm 02 03 4233.1
END DESCRIPTION:
XS GIS Cut Line= 3
      1610215.58      6817609.10      1610656.11      6817624.29
      1610998.99      6817639.48
#Sta/Elev= 30
  4559.0 1820.79  4588.4 1820.69  4628.5 1821.07  4648.5 1820.81  4672.9 1821.10
  4678.5 1820.81  4708.5 1820.93  4748.5 1820.30  4758.5 1819.77  4798.6 1819.50
  4848.6 1817.93  4858.6 1817.91  4898.6 1816.17  4908.6 1816.40  4928.6 1815.32
  4963.0 1814.21  4966.7 1813.70  4966.9 1813.20  4970.4 1813.20  4970.7 1813.70
  5018.7 1813.84  5048.7 1814.58  5068.7 1814.58  5108.8 1815.46  5118.8 1815.97
  5138.8 1816.16  5158.8 1816.76  5258.9 1818.07  5299.0 1819.08  5343.0 1819.62
#Mann=3,-1,0
  4559.0    0.05       0  4966.7    0.05       0  4970.7    0.05       0
Bank Sta=4966.7,4970.7
Exp/Cntr=0.3,0.1

Type RM Length L Ch R = 1,4041,229,229,229
BEGIN DESCRIPTION:
Elm 02 03 4041.16
END DESCRIPTION:
XS GIS Cut Line= 3
      1610183.04      6817800.07      1610625.73      6817771.86
      1611137.90      6817778.37
#Sta/Elev= 30
  4561.3 1819.69  4675.5 1820.36  4743.6 1819.88  4753.6 1819.33  4773.7 1818.87
  4783.7 1818.25  4823.8 1816.91  4829.2 1816.54  4834.2 1816.73  4883.9 1815.01
  4914.0 1813.13  4924.0 1812.81  4981.0 1812.47  4981.3 1811.97  4984.8 1811.97
  4985.0 1812.47  4988.0 1812.70  5014.2 1813.05  5044.2 1812.89  5092.0 1814.94
  5164.2 1816.51  5234.2 1817.43  5254.2 1818.03  5274.2 1818.22  5284.2 1818.63
  5314.2 1819.18  5364.2 1819.66  5374.2 1820.01  5394.2 1820.07  5517.1 1821.97
#Mann=3,-1,0
  4561.3    0.05       0  4981.0    0.03       0  4985.0    0.05       0
Bank Sta=4981,4985
Exp/Cntr=0.3,0.1

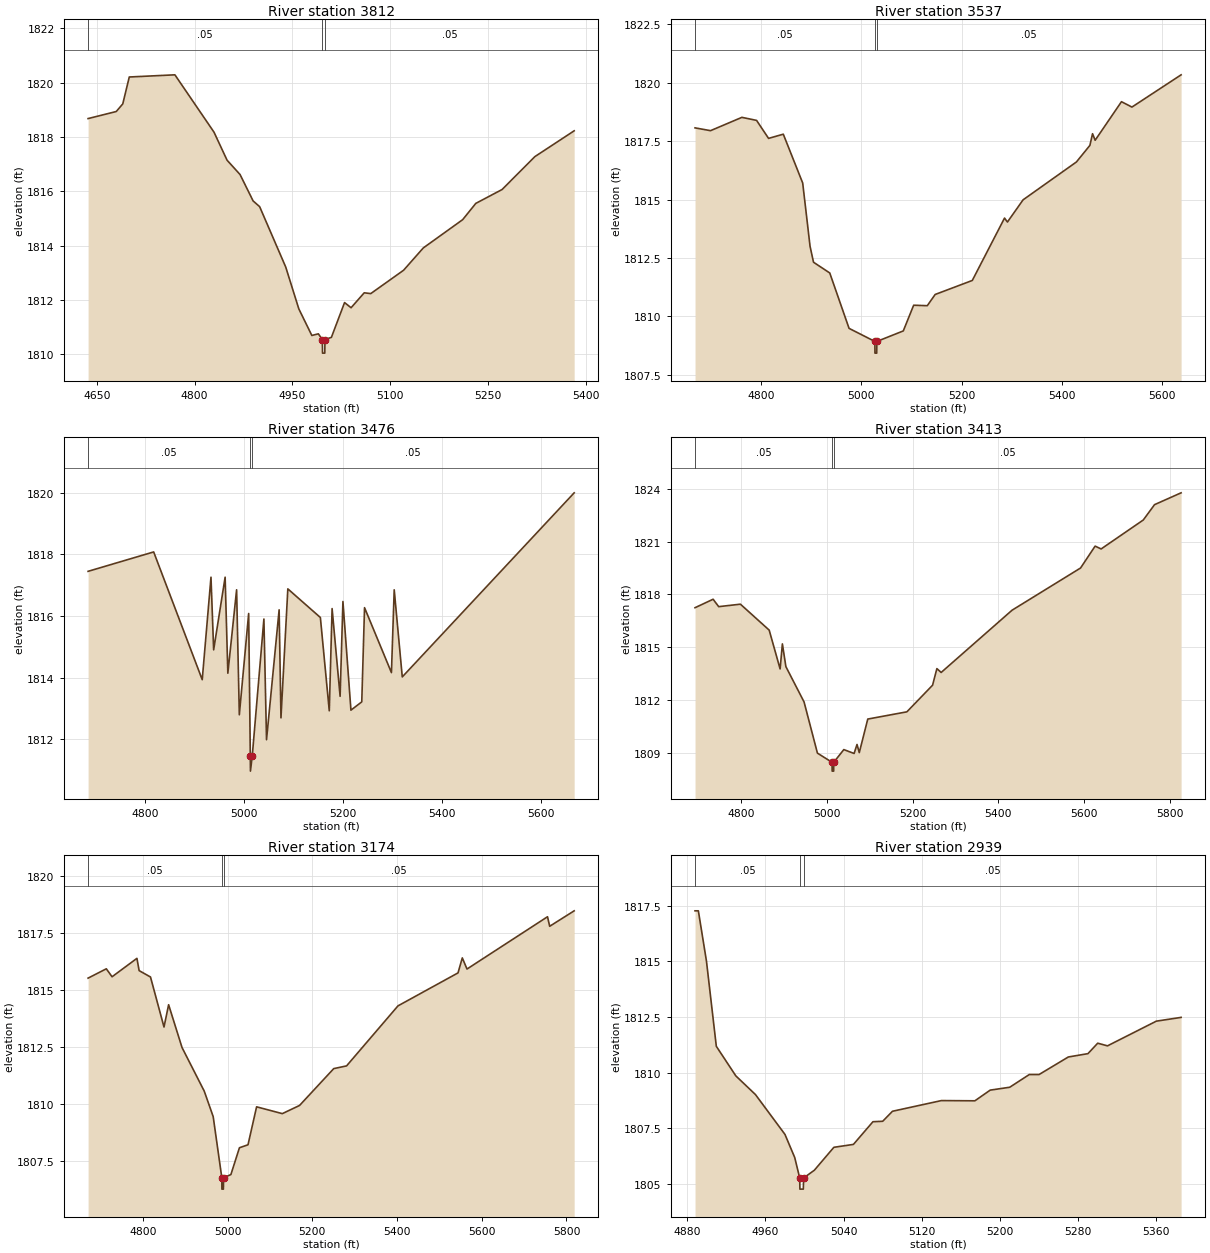
Type RM Length L Ch R = 1,3812,275,275,275
BEGIN DESCRIPTION:
Elm 02 03 3811.52
END DESCRIPTION:
XS GIS Cut Line= 3
      1610141.76      6817958.78      1610506.37      6817962.25
      1610884.87      6817917.11
#Sta/Elev= 30
  4636.6 1818.68  4679.8 1818.94  4689.8 1819.22  4699.8 1820.21  4769.8 1820.29
  4829.8 1818.18  4849.8 1817.15  4869.8 1816.62  4889.8 1815.65  4899.8 1815.44
  4939.8 1813.22  4959.9 1811.68  4979.9 1810.70  4989.9 1810.76  4996.0 1810.55
  4996.3 1810.05  4999.8 1810.05  5000.0 1810.55  5009.9 1810.63  5030.1 1811.91
  5040.1 1811.72  5060.3 1812.27  5070.3 1812.24  5120.7 1813.10  5150.9 1813.92
  5211.3 1814.96  5231.5 1815.56  5271.8 1816.07  5322.1 1817.28  5382.4 1818.23
#Mann=3,-1,0
  4636.6    0.05       0  4996.0    0.03       0  5000.0    0.05       0
Bank Sta=4996,5000
Exp/Cntr=0.3,0.1

Type RM Length L Ch R = 1,3537,61,61,61
BEGIN DESCRIPTION:
Mapping XS 8a4e4ad3
END DESCRIPTION:
XS GIS Cut Line= 6
      1610106.44      6818066.05      1610295.29      6818144.19
      1610440.69      6818202.79      1610505.79      6818200.62
      1610740.17      6818061.73      1610998.40      6817979.26
#Sta/Elev= 30
  4668.2 1818.07  4699.1 1817.95  4761.7 1818.52  4791.0 1818.39  4814.9 1817.62
  4844.3 1817.80  4883.0 1815.71  4897.7 1813.00  4904.6 1812.32  4937.0 1811.86
  4975.5 1809.49  5027.0 1808.93  5027.2 1808.43  5030.7 1808.43  5031.0 1808.93
  5083.7 1809.38  5104.4 1810.48  5131.6 1810.46  5147.3 1810.94  5221.4 1811.54
  5285.7 1814.21  5291.5 1814.04  5322.7 1814.99  5429.1 1816.61  5456.0 1817.32
  5461.3 1817.82  5466.5 1817.54  5519.0 1819.19  5539.9 1818.96  5638.0 1820.34
#Mann=3,-1,0
  4668.2    0.05       0  5027.0    0.05       0  5031.0    0.05       0
Bank Sta=5027,5031
Exp/Cntr=0.3,0.1

Type RM Length L Ch R = 1,3476,63,63,63
BEGIN DESCRIPTION:
Elm 02 03 3475.52
END DESCRIPTION:
XS GIS Cut Line= 5
      1610077.56      6818099.41      1610364.01      6818227.88
      1610436.93      6818253.92      1610527.20      6818246.97
      1610968.15      6818009.14
#Sta/Elev= 30
  4684.4 1817.45  4817.0 1818.08  4915.2 1813.93  4932.9 1817.26  4938.3 1814.90
  4961.5 1817.26  4967.0 1814.14  4984.7 1816.85  4990.2 1812.79  5009.1 1816.08
  5012.4 1811.46  5012.7 1810.96  5016.4 1811.46  5039.9 1815.90  5045.2 1811.98
  5070.7 1816.20  5074.4 1812.69  5088.3 1816.88  5154.1 1815.95  5172.1 1812.92
  5177.8 1816.24  5194.0 1813.39  5199.7 1816.47  5215.9 1812.94  5237.8 1813.21
  5243.4 1816.27  5297.8 1814.16  5303.4 1816.85  5319.7 1814.02  5667.3 1820.00
#Mann=3,-1,0
  4684.4    0.05       0  5012.4    0.05       0  5016.4    0.05       0
Bank Sta=5012.4,5016.4
Exp/Cntr=0.3,0.1

Type RM Length L Ch R = 1,3413,239,239,239
BEGIN DESCRIPTION:
Mapping XS 925de3c3
END DESCRIPTION:
XS GIS Cut Line= 4
      1610065.28      6818185.43      1610466.73      6818328.65
      1610631.66      6818326.48      1611154.66      6818178.92
#Sta/Elev= 30
  4692.3 1817.25  4734.5 1817.73  4747.5 1817.31  4798.2 1817.45  4865.4 1815.98
  4890.9 1813.78  4896.2 1815.20  4904.4 1813.91  4946.8 1811.91  4978.0 1809.01
  5012.1 1808.49  5012.4 1807.99  5015.9 1807.99  5016.1 1808.49  5039.6 1809.21
  5063.6 1808.99  5070.4 1809.50  5075.7 1809.04  5095.5 1810.94  5186.8 1811.35
  5246.8 1812.86  5256.8 1813.80  5266.8 1813.58  5432.4 1817.11  5592.2 1819.50
  5626.2 1820.74  5640.2 1820.58  5738.6 1822.22  5764.9 1823.09  5826.9 1823.76
#Mann=3,-1,0
  4692.3    0.05       0  5012.1    0.03       0  5016.1    0.05       0
Bank Sta=5012.1,5016.1
Exp/Cntr=0.3,0.1

Type RM Length L Ch R = 1,3174,235,235,235
BEGIN DESCRIPTION:
Elm 02 03 3173.65
END DESCRIPTION:
XS GIS Cut Line= 3
      1609944.12      6818396.24      1610258.74      6818498.22
      1611066.08      6818621.92
#Sta/Elev= 30
  4670.7 1815.53  4713.7 1815.94  4727.3 1815.59  4786.0 1816.40  4791.2 1815.86
  4818.0 1815.58  4849.9 1813.38  4860.8 1814.36  4892.4 1812.48  4944.9 1810.56
  4966.0 1809.44  4986.4 1806.75  4986.6 1806.25  4990.1 1806.25  4990.4 1806.75
  5007.8 1806.89  5028.0 1808.07  5048.2 1808.20  5068.5 1809.87  5129.2 1809.57
  5169.9 1809.93  5250.6 1811.55  5280.9 1811.67  5402.3 1814.31  5544.0 1815.76
  5554.1 1816.42  5565.2 1815.93  5755.3 1818.23  5760.4 1817.81  5818.2 1818.49
#Mann=3,-1,0
  4670.7    0.05       0  4986.4    0.05       0  4990.4    0.05       0
Bank Sta=4986.4,4990.4
Exp/Cntr=0.3,0.1

Type RM Length L Ch R = 1,2939,209,209,209
BEGIN DESCRIPTION:
Elm 02 03 2939.07
END DESCRIPTION:
XS GIS Cut Line= 3
      1610093.33      6818706.11      1610204.05      6818716.53
      1610590.38      6818730.84
#Sta/Elev= 30
  4887.9 1817.27  4891.3 1817.27  4899.6 1815.01  4909.7 1811.18  4929.7 1809.85
  4949.8 1809.01  4980.0 1807.22  4990.0 1806.18  4995.1 1805.26  4995.3 1804.76
  4998.8 1804.76  4999.1 1805.26  5010.1 1805.61  5030.1 1806.64  5050.1 1806.77
  5070.1 1807.79  5080.1 1807.81  5090.1 1808.26  5140.2 1808.74  5174.5 1808.73
  5190.2 1809.21  5210.2 1809.34  5230.2 1809.91  5240.2 1809.91  5270.2 1810.70
  5290.3 1810.85  5300.3 1811.32  5310.3 1811.20  5360.3 1812.31  5385.7 1812.48
#Mann=3,-1,0
  4887.9    0.05       0  4995.1    0.05       0  4999.1    0.05       0
Bank Sta=4995.1,4999.1
Exp/Cntr=0.3,0.1

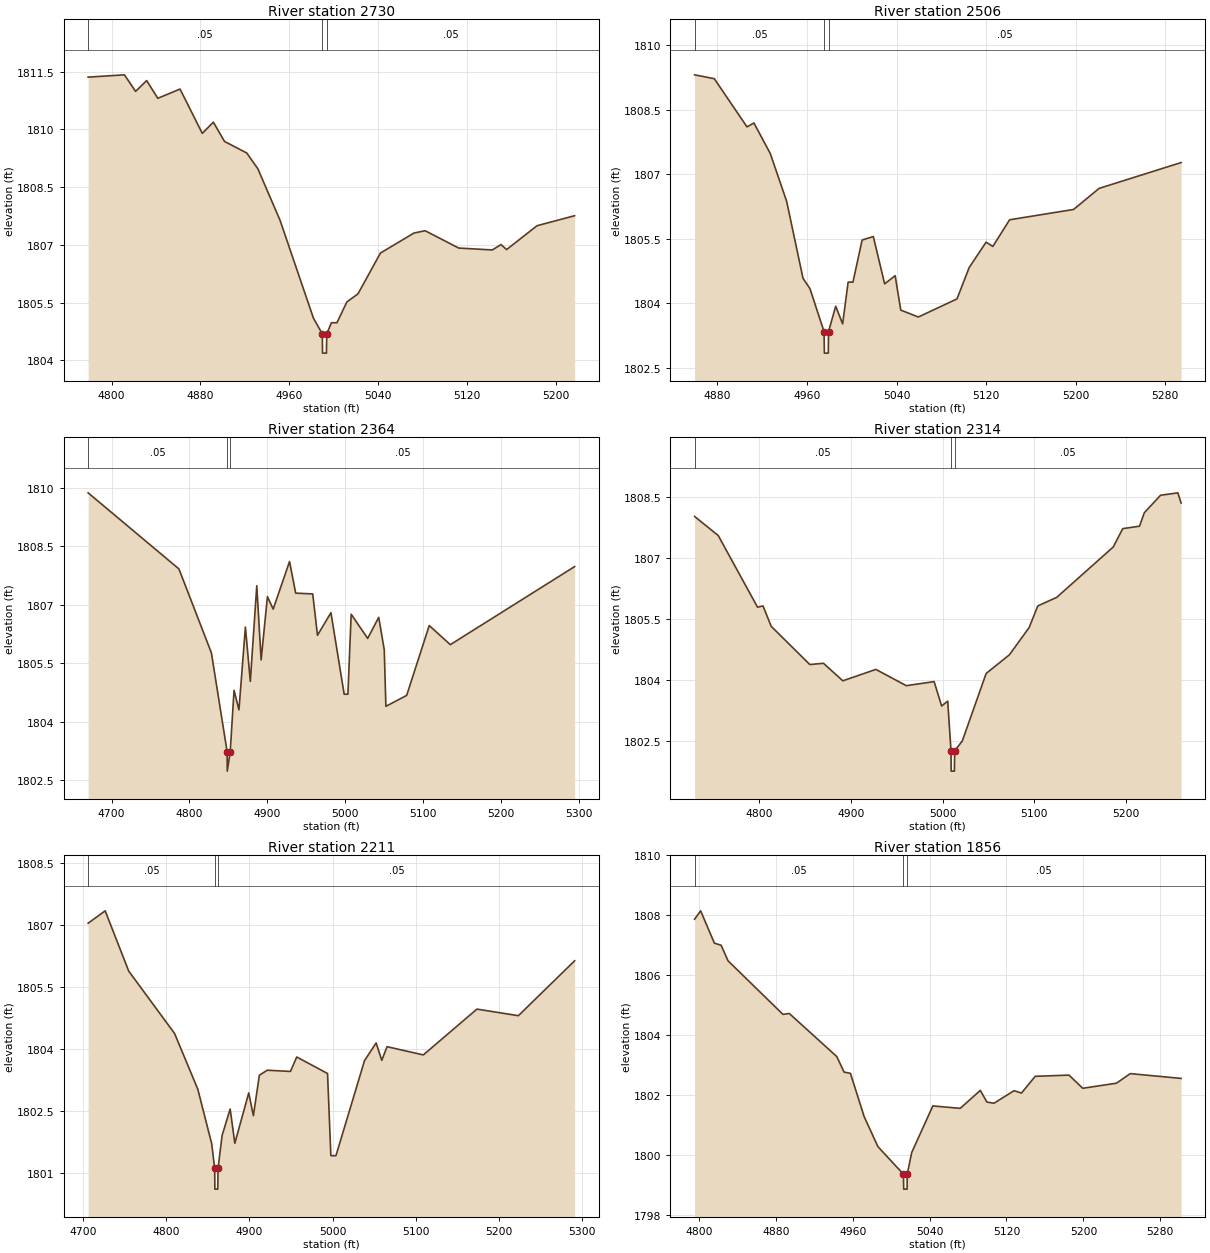
Type RM Length L Ch R = 1,2730,224,224,224
BEGIN DESCRIPTION:
Elm 02 03 2729.75
END DESCRIPTION:
XS GIS Cut Line= 3
      1609932.31      6818910.54      1610152.41      6818910.54
      1610368.60      6818885.80
#Sta/Elev= 30
  4778.9 1811.36  4811.6 1811.42  4821.6 1810.99  4831.6 1811.27  4841.6 1810.81
  4861.6 1811.05  4881.6 1809.90  4891.6 1810.19  4901.6 1809.69  4921.6 1809.39
  4931.6 1808.98  4951.6 1807.64  4981.6 1805.10  4989.6 1804.69  4989.8 1804.19
  4993.3 1804.19  4993.6 1804.69  4997.8 1804.98  5002.8 1804.98  5011.7 1805.52
  5021.7 1805.73  5041.9 1806.79  5072.1 1807.31  5082.1 1807.37  5112.3 1806.92
  5142.5 1806.87  5150.4 1807.01  5155.4 1806.88  5182.8 1807.50  5216.6 1807.76
#Mann=3,-1,0
  4778.9    0.05       0  4989.6    0.05       0  4993.6    0.05       0
Bank Sta=4989.6,4993.6
Exp/Cntr=0.3,0.1

Type RM Length L Ch R = 1,2506,142,142,142
BEGIN DESCRIPTION:
Elm 02 03 2506.39
END DESCRIPTION:
XS GIS Cut Line= 4
      1609993.56      6819034.25      1610106.83      6819118.88
      1610199.28      6819127.99      1610365.98      6819017.29
#Sta/Elev= 30
  4859.7 1809.31  4877.3 1809.22  4906.5 1808.10  4912.7 1808.19  4927.3 1807.48
  4941.9 1806.37  4956.5 1804.58  4962.7 1804.34  4975.3 1803.34  4975.6 1802.84
  4979.1 1802.84  4979.3 1803.34  4985.7 1803.93  4991.9 1803.52  4996.8 1804.49
  5001.1 1804.49  5009.3 1805.47  5019.3 1805.55  5029.4 1804.45  5038.8 1804.64
  5043.8 1803.84  5059.5 1803.68  5094.0 1804.10  5104.9 1804.83  5120.0 1805.42
  5126.0 1805.32  5141.0 1805.94  5198.1 1806.18  5220.9 1806.67  5294.1 1807.27
#Mann=3,-1,0
  4859.7    0.05       0  4975.3    0.05       0  4979.3    0.05       0
Bank Sta=4975.3,4979.3
Exp/Cntr=0.3,0.1

Type RM Length L Ch R = 1,2364,50,50,50
BEGIN DESCRIPTION:
Elm 02 03 2363.79
END DESCRIPTION:
XS GIS Cut Line= 6
      1609920.67      6819049.89      1610099.02      6819183.98
      1610160.22      6819225.65      1610194.07      6819226.95
      1610230.53      6819190.49      1610423.27      6819043.33
#Sta/Elev= 30
  4669.8 1809.87  4786.5 1807.92  4828.2 1805.77  4848.4 1803.24  4848.6 1802.74
  4852.4 1803.24  4857.3 1804.81  4863.6 1804.31  4871.9 1806.43  4878.2 1805.04
  4886.5 1807.49  4892.1 1805.59  4900.2 1807.21  4907.6 1806.89  4928.6 1808.11
  4936.5 1807.30  4958.4 1807.28  4964.5 1806.22  4981.8 1806.80  4998.8 1804.71
  5003.6 1804.71  5007.8 1806.76  5029.0 1806.14  5043.2 1806.68  5050.3 1805.85
  5052.4 1804.40  5079.1 1804.68  5108.1 1806.47  5135.2 1805.98  5294.9 1807.98
#Mann=3,-1,0
  4669.8    0.05       0  4848.4    0.05       0  4852.4    0.05       0
Bank Sta=4848.4,4852.4
Exp/Cntr=0.3,0.1

Type RM Length L Ch R = 1,2314,103,103,103
BEGIN DESCRIPTION:
Elm 02 03 2314.33
END DESCRIPTION:
XS GIS Cut Line= 4
      1609963.56      6819164.42      1610102.93      6819258.20
      1610205.79      6819273.82      1610456.81      6819213.01
#Sta/Elev= 30
  4729.6 1808.02  4755.4 1807.55  4798.2 1805.79  4804.2 1805.82  4813.1 1805.32
  4855.2 1804.38  4870.1 1804.41  4891.2 1803.98  4927.2 1804.26  4960.4 1803.86
  4990.7 1803.96  4998.9 1803.36  5005.5 1803.48  5009.1 1802.26  5009.3 1801.76
  5012.8 1801.76  5013.1 1802.26  5021.4 1802.50  5047.4 1804.16  5072.8 1804.62
  5094.3 1805.29  5103.7 1805.82  5124.3 1806.03  5186.0 1807.27  5196.3 1807.72
  5214.6 1807.78  5219.8 1808.11  5237.5 1808.54  5256.4 1808.60  5259.9 1808.35
#Mann=3,-1,0
  4729.6    0.05       0  5009.1    0.05       0  5013.1    0.05       0
Bank Sta=5009.1,5013.1
Exp/Cntr=0.3,0.1

Type RM Length L Ch R = 1,2211,355,355,355
BEGIN DESCRIPTION:
Elm 02 03 2210.89
END DESCRIPTION:
XS GIS Cut Line= 3
      1609941.45      6819243.87      1610203.19      6819376.69
      1610434.49      6819553.41
#Sta/Elev= 30
  4706.2 1807.05  4726.7 1807.35  4755.0 1805.89  4810.1 1804.38  4838.0 1803.03
  4854.7 1801.71  4858.3 1801.11  4858.5 1800.61  4862.0 1800.61  4862.3 1801.11
  4867.2 1801.91  4876.9 1802.55  4882.5 1801.72  4899.2 1802.94  4904.8 1802.39
  4912.0 1803.37  4921.5 1803.49  4949.3 1803.46  4956.9 1803.81  4993.9 1803.41
  4997.9 1801.42  5004.0 1801.42  5038.3 1803.72  5052.3 1804.15  5059.1 1803.73
  5065.4 1804.06  5109.0 1803.86  5173.4 1804.97  5223.2 1804.81  5290.8 1806.14
#Mann=3,-1,0
  4706.2    0.05       0  4858.3    0.05       0  4862.3    0.05       0
Bank Sta=4858.3,4862.3
Exp/Cntr=0.3,0.1

Type RM Length L Ch R = 1,1856,241,241,241
BEGIN DESCRIPTION:
Elm 02 03 1941.432
END DESCRIPTION:
XS GIS Cut Line= 3
      1609846.91      6819307.06      1609980.03      6819462.17
      1610175.57      6819691.79
#Sta/Elev= 30
  4795.6 1807.87  4801.9 1808.15  4816.2 1807.07  4823.2 1807.00  4830.4 1806.48
  4887.5 1804.69  4894.1 1804.72  4943.5 1803.28  4951.1 1802.76  4957.7 1802.72
  4972.0 1801.27  4986.3 1800.27  5012.8 1799.35  5013.1 1798.85  5016.6 1798.85
  5016.8 1799.35  5021.4 1800.07  5043.4 1801.63  5071.9 1801.55  5092.8 1802.15
  5099.6 1801.76  5107.0 1801.72  5127.9 1802.14  5135.6 1802.06  5149.9 1802.62
  5185.0 1802.66  5199.3 1802.22  5234.4 1802.39  5248.7 1802.71  5301.6 1802.55
#Mann=3,-1,0
  4795.6    0.05       0  5012.8    0.05       0  5016.8    0.05       0
Bank Sta=5012.8,5016.8
Exp/Cntr=0.3,0.1

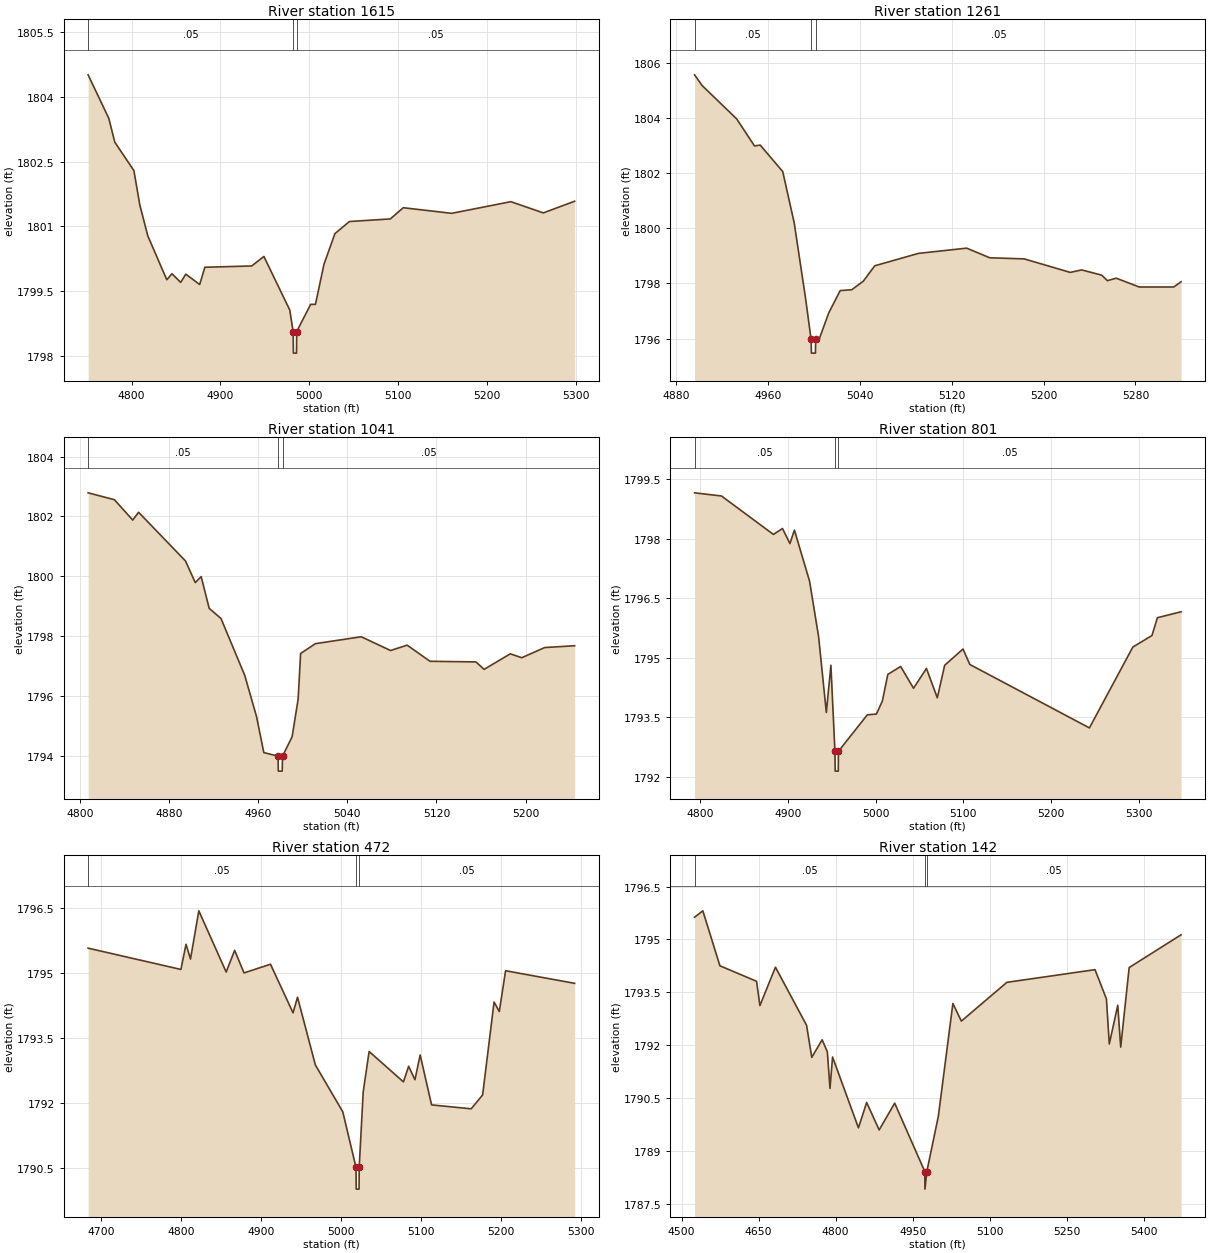
Type RM Length L Ch R = 1,1615,354,354,354
BEGIN DESCRIPTION:
Elm 02 03 1614.56
END DESCRIPTION:
XS GIS Cut Line= 3
      1609714.20      6819437.97      1609841.96      6819653.21
      1609965.50      6819923.19
#Sta/Elev= 30
  4751.2 1804.51  4774.5 1803.50  4781.2 1802.95  4802.7 1802.29  4809.4 1801.49
  4818.3 1800.78  4839.7 1799.76  4845.5 1799.90  4855.3 1799.70  4861.1 1799.89
  4876.7 1799.65  4882.5 1800.05  4935.2 1800.08  4948.9 1800.30  4978.0 1799.06
  4981.8 1798.56  4982.1 1798.06  4985.6 1798.06  4985.8 1798.56  5001.5 1799.19
  5006.9 1799.19  5016.5 1800.12  5028.8 1800.83  5045.1 1801.11  5091.1 1801.17
  5105.7 1801.43  5160.1 1801.30  5226.7 1801.57  5263.2 1801.31  5298.4 1801.58
#Mann=3,-1,0
  4751.2    0.05       0  4981.8    0.05       0  4985.8    0.05       0
Bank Sta=4981.8,4985.8
Exp/Cntr=0.3,0.1

Type RM Length L Ch R = 1,1261,220,220,220
BEGIN DESCRIPTION:
Elm 02 03 1260.77
END DESCRIPTION:
XS GIS Cut Line= 3
      1609614.18      6819441.46      1609605.85      6819546.31
      1609585.79      6819864.40
#Sta/Elev= 30
  4895.9 1805.57  4902.5 1805.18  4932.6 1803.97  4948.1 1802.99  4953.1 1803.02
  4972.7 1802.06  4982.7 1800.20  4992.7 1797.43  4997.4 1795.97  4997.7 1795.47
  5001.2 1795.47  5001.4 1795.97  5004.4 1795.97  5012.8 1796.93  5022.8 1797.74
  5032.8 1797.77  5042.9 1798.08  5052.9 1798.64  5091.0 1799.09  5133.0 1799.28
  5153.1 1798.93  5183.1 1798.89  5223.2 1798.40  5233.2 1798.49  5250.6 1798.30
  5255.6 1798.10  5263.3 1798.19  5283.3 1797.87  5313.4 1797.87  5319.8 1798.06
#Mann=3,-1,0
  4895.9    0.05       0  4997.4    0.05       0  5001.4    0.05       0
Bank Sta=4997.4,5001.4
Exp/Cntr=0.3,0.1

Type RM Length L Ch R = 1,1041,240,240,240
BEGIN DESCRIPTION:
Elm 02 03 1040.61
END DESCRIPTION:
XS GIS Cut Line= 3
      1609376.36      6819505.77      1609441.48      6819687.24
      1609498.53      6819924.07
#Sta/Elev= 30
  4807.5 1802.79  4831.1 1802.56  4847.5 1801.88  4852.8 1802.14  4894.9 1800.51
  4903.6 1799.79  4908.9 1799.99  4916.1 1798.93  4926.7 1798.59  4948.0 1796.69
  4958.6 1795.31  4965.1 1794.11  4977.9 1793.99  4978.1 1793.49  4981.6 1793.49
  4981.9 1793.99  4990.5 1794.64  4995.9 1795.90  4998.1 1797.42  5011.4 1797.75
  5052.5 1797.98  5078.8 1797.52  5093.7 1797.70  5114.2 1797.16  5155.4 1797.14
  5162.7 1796.89  5186.2 1797.41  5196.5 1797.28  5217.1 1797.62  5243.9 1797.68
#Mann=3,-1,0
  4807.5    0.05       0  4977.9    0.05       0  4981.9    0.05       0
Bank Sta=4977.9,4981.9
Exp/Cntr=0.3,0.1

Type RM Length L Ch R = 1,801,329,329,329
BEGIN DESCRIPTION:
Elm 02 03 800.66
END DESCRIPTION:
XS GIS Cut Line= 3
      1609153.29      6819480.67      1609202.76      6819682.03
      1609407.63      6819962.41
#Sta/Elev= 30
  4793.6 1799.16  4824.3 1799.08  4883.5 1798.11  4893.8 1798.26  4902.3 1797.88
  4907.4 1798.22  4924.7 1796.93  4935.0 1795.53  4943.8 1793.62  4949.0 1794.81
  4953.6 1792.64  4953.9 1792.14  4957.4 1792.14  4957.6 1792.64  4990.5 1793.56
  5000.9 1793.58  5007.7 1793.91  5013.9 1794.58  5028.5 1794.78  5043.2 1794.23
  5057.9 1794.73  5070.3 1793.99  5078.7 1794.81  5099.6 1795.22  5107.4 1794.83
  5243.7 1793.23  5293.2 1795.27  5315.0 1795.56  5321.2 1796.01  5348.2 1796.16
#Mann=3,-1,0
  4793.6    0.05       0  4953.6    0.05       0  4957.6    0.05       0
Bank Sta=4953.6,4957.6
Exp/Cntr=0.3,0.1

Type RM Length L Ch R = 1,472,330,330,330
BEGIN DESCRIPTION:
Elm 02 03 472.05
END DESCRIPTION:
XS GIS Cut Line= 3
      1608934.53      6819534.45      1609076.90      6819816.58
      1609263.52      6820041.40
#Sta/Elev= 30
  4683.9 1795.57  4799.9 1795.08  4806.3 1795.66  4811.9 1795.32  4822.3 1796.43
  4856.5 1795.02  4867.1 1795.52  4878.8 1795.00  4911.9 1795.20  4940.1 1794.08
  4945.7 1794.44  4968.0 1792.88  5002.3 1791.80  5018.8 1790.52  5019.1 1790.02
  5022.6 1790.02  5022.8 1790.52  5027.8 1792.26  5035.2 1793.19  5078.1 1792.49
  5084.6 1792.85  5092.5 1792.54  5099.0 1793.11  5113.3 1791.96  5162.8 1791.87
  5177.1 1792.19  5191.4 1794.33  5197.9 1794.11  5205.8 1795.05  5292.1 1794.76
#Mann=3,-1,0
  4683.9    0.05       0  5018.8    0.05       0  5022.8    0.05       0
Bank Sta=5018.8,5022.8
Exp/Cntr=0.3,0.1

Type RM Length L Ch R = 1,142,0,0,0
BEGIN DESCRIPTION:
Elm 02 03 1445.114
END DESCRIPTION:
XS GIS Cut Line= 3
      1608876.51      6819512.01      1608810.81      6819982.14
      1609230.96      6820198.76
#Sta/Elev= 30
  4525.3 1795.63  4541.4 1795.81  4574.6 1794.25  4646.0 1793.81  4652.5 1793.12
  4682.8 1794.21  4743.4 1792.56  4753.5 1791.65  4773.7 1792.15  4783.8 1791.81
  4789.0 1790.77  4794.0 1791.66  4844.4 1789.65  4860.4 1790.37  4884.7 1789.59
  4915.0 1790.35  4973.6 1788.41  4973.9 1787.91  4977.6 1788.41  5000.0 1789.98
  5028.3 1793.18  5044.8 1792.68  5133.5 1793.78  5305.1 1794.14  5327.3 1793.31
  5332.9 1792.03  5349.4 1793.13  5355.1 1791.94  5371.6 1794.20  5472.7 1795.13
#Mann=3,-1,0
  4525.3    0.05       0  4973.6    0.05       0  4977.6    0.05       0
Bank Sta=4973.6,4977.6
Exp/Cntr=0.3,0.1

Chan Stop Cuts=-1