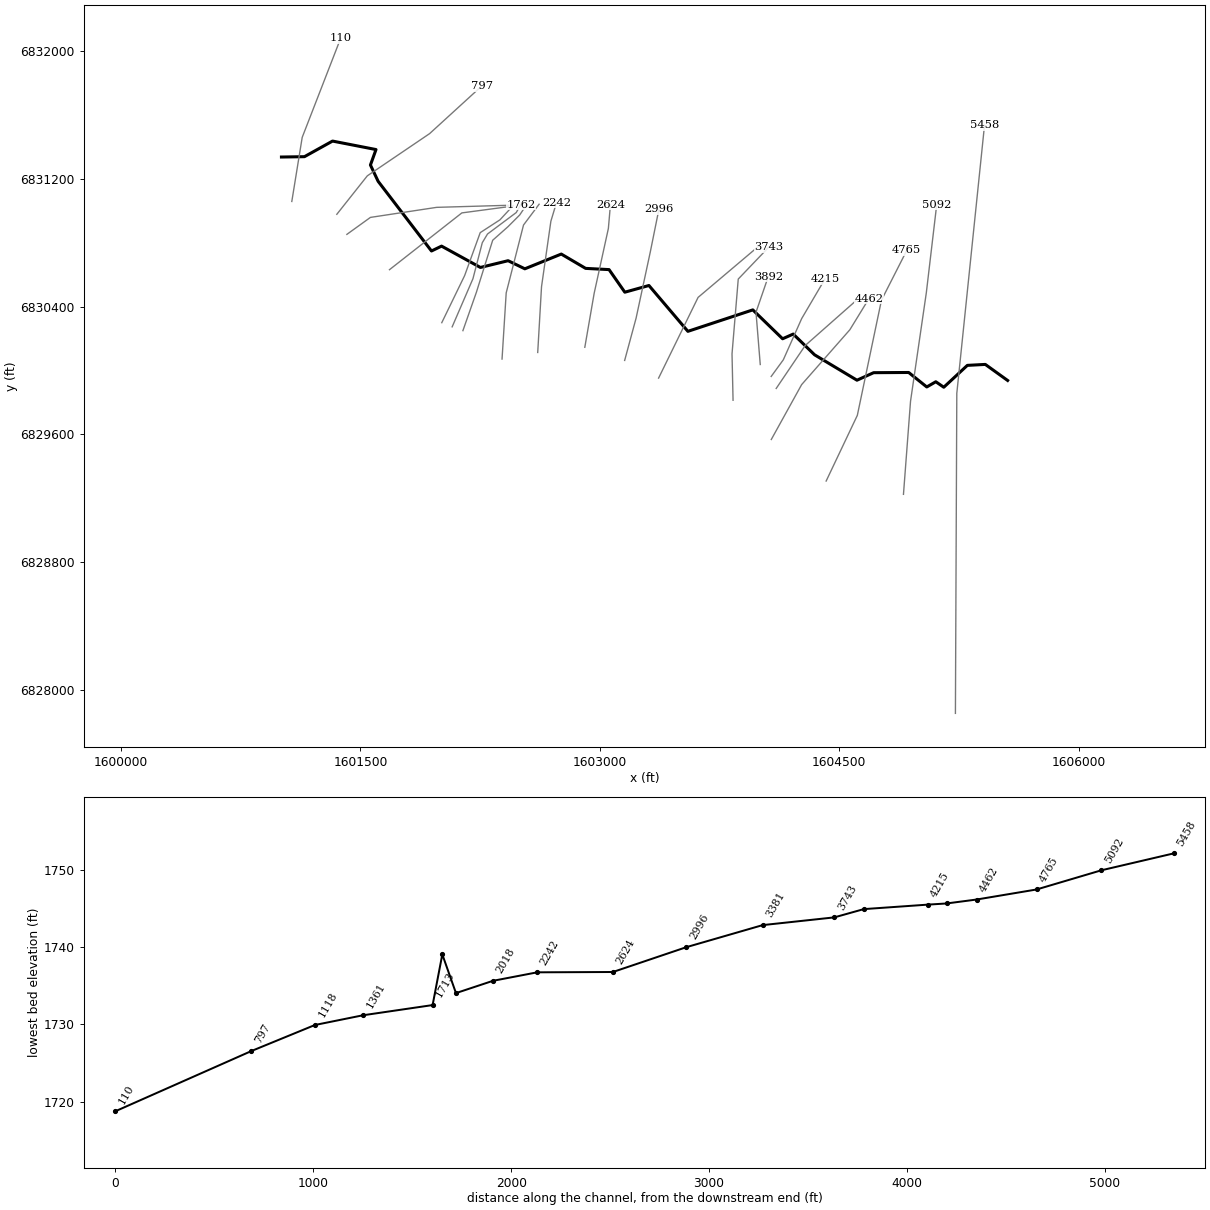
--- Elm 02 04.prj (project) ---

Proj Title=Elm 02 04 Base Level Engineering
Current Plan=p01
Default Exp/Contr=0.3,0.1
English Units
Geom File=g01
Flow File=f01
Plan File=p01
BEGIN DESCRIPTION:
Elm 02 04
END DESCRIPTION:

--- Elm 02 04.p01 (plan) ---

Plan Title=Multiple Run
Short Identifier=Multiple
Geom File=g01
Flow File=f01
Subcritical Flow
K Sum by GR= 0
Std Step Tol= 0.01
Critical Tol= 0.01
Num of Std Step Trials= 20
Max Error Tol= 0.3
Flow Tol Ratio= 0.001
Split Flow NTrial= 30
Split Flow Tol= 0.02
Split Flow Ratio= 0.02
Log Output Level= 0
Friction Slope Method= 1
Unsteady Friction Slope Method= 2
Unsteady Bridges Friction Slope Method= 1
Parabolic Critical Depth
Global Vel Dist=  1 , 1 , 1
Global Log Level= 0
CheckData=True
Encroach Param= -1, 0, 0, 0
BEGIN DESCRIPTION:
Multiple Run
END DESCRIPTION:

--- Elm 02 04.f01 (steady flow) ---

Flow Title=Multiple
Number of Profiles=7
Profile Names=10-year,25-year,50-year,1pct_min,100-year,1pct_plu,500-year
River Rch & RM= Elm 02 04,Reach-1,5458
     142     189     226     168     269     370     386
Boundary for River Rch & Prof#=Elm 02 04,Reach-1,1
Up Type=0
Dn Type=3
Dn Slope=0.001
Boundary for River Rch & Prof#=Elm 02 04,Reach-1,2
Up Type=0
Dn Type=3
Dn Slope=0.001
Boundary for River Rch & Prof#=Elm 02 04,Reach-1,3
Up Type=0
Dn Type=3
Dn Slope=0.001
Boundary for River Rch & Prof#=Elm 02 04,Reach-1,4
Up Type=0
Dn Type=3
Dn Slope=0.001
Boundary for River Rch & Prof#=Elm 02 04,Reach-1,5
Up Type=0
Dn Type=3
Dn Slope=0.001
Boundary for River Rch & Prof#=Elm 02 04,Reach-1,6
Up Type=0
Dn Type=3
Dn Slope=0.001
Boundary for River Rch & Prof#=Elm 02 04,Reach-1,7
Up Type=0
Dn Type=3
Dn Slope=0.001

--- Elm 02 04.g01 (geometry) ---

Geom Title=Existing Conditions

River Reach=Elm 02 04,Reach-1
Reach XY= 30
      1605555.00      6829938.00      1605415.18      6830038.55
      1605302.55      6830032.55      1605155.00      6829895.54
      1605105.00      6829929.95      1605048.34      6829897.31
      1604935.02      6829988.03      1604715.50      6829986.76
      1604611.04      6829939.63      1604345.32      6830098.77
      1604211.67      6830228.70      1604145.00      6830199.24
      1603958.42      6830380.21      1603551.58      6830245.79
      1603307.55      6830533.01      1603156.42      6830491.04
      1603057.70      6830632.63      1602910.93      6830640.25
      1602758.32      6830729.96      1602530.00      6830637.60
      1602425.14      6830688.38      1602251.68      6830646.04
      1602008.23      6830779.75      1601944.98      6830749.23
      1601610.82      6831185.72      1601562.57      6831288.03
      1601597.40      6831384.84      1601325.03      6831437.96
      1601149.09      6831340.20      1601005.00      6831338.00

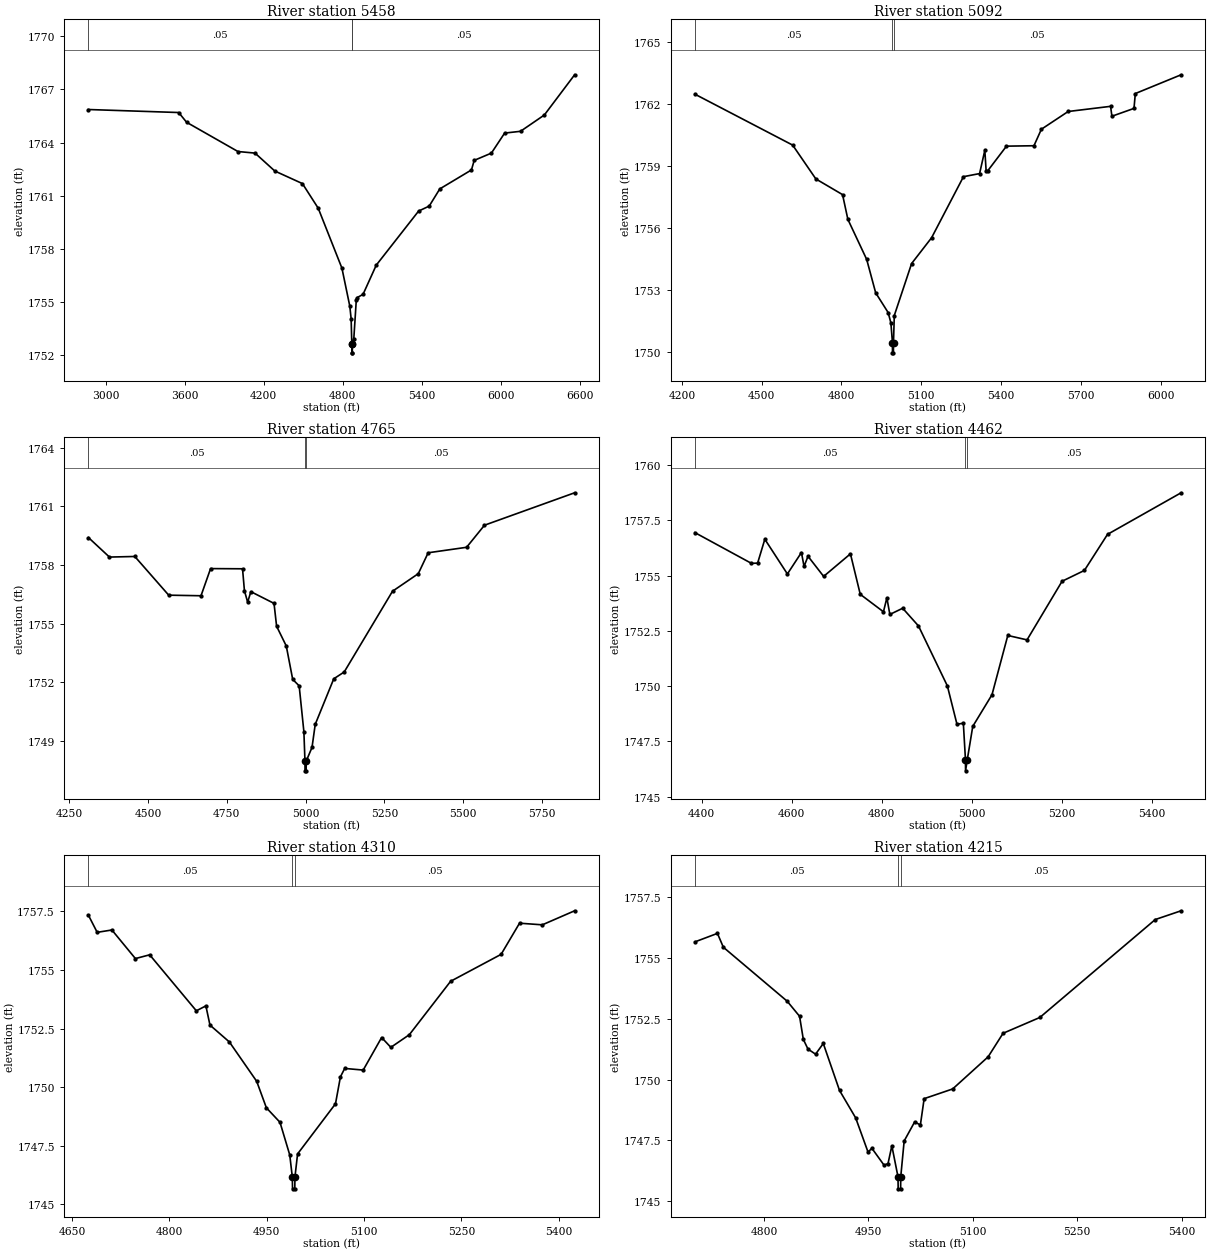
Type RM Length L Ch R = 1,5458,366,366,366
BEGIN DESCRIPTION:
Elm 02 04 5691.983
END DESCRIPTION:
XS GIS Cut Line= 3
      1605227.86      6827852.07      1605236.54      6829857.28
      1605410.15      6831537.01
#Sta/Elev= 30
  2868.6 1765.87  3554.5 1765.70  3614.5 1765.15  4004.5 1763.50  4134.5 1763.41
  4284.5 1762.40  4494.5 1761.69  4614.5 1760.30  4794.5 1756.92  4854.5 1754.77
  4864.5 1754.06  4869.7 1752.64  4869.9 1752.14  4873.4 1752.14  4873.7 1752.64
  4884.6 1752.91  4903.6 1755.11  4908.6 1755.25  4955.0 1755.44  5055.5 1757.09
  5377.2 1760.14  5457.6 1760.42  5538.1 1761.39  5778.6 1762.46  5799.5 1763.00
  5930.1 1763.41  6030.7 1764.54  6151.3 1764.64  6332.3 1765.56  6562.5 1767.83
#Mann=3,-1,0
  2868.6    0.05       0  4869.7    0.03       0  4873.7    0.05       0
Bank Sta=4869.7,4873.7
Exp/Cntr=0.3,0.1

Type RM Length L Ch R = 1,5092,327,327,327
BEGIN DESCRIPTION:
Mapping XS 6187e469
END DESCRIPTION:
XS GIS Cut Line= 4
      1604902.34      6829224.51      1604946.61      6829807.81
      1605045.56      6830487.49      1605110.66      6831039.54
#Sta/Elev= 30
  4249.1 1762.49  4616.7 1760.02  4703.9 1758.38  4804.2 1757.62  4824.2 1756.42
  4894.9 1754.48  4928.7 1752.86  4975.7 1751.90  4985.9 1751.40  4991.7 1750.45
  4991.9 1749.95  4995.4 1749.95  4995.7 1750.45  4998.7 1751.76  5063.8 1754.28
  5138.9 1755.53  5258.7 1758.49  5319.3 1758.64  5339.0 1759.77  5344.0 1758.75
  5349.6 1758.77  5420.4 1759.97  5523.7 1759.99  5551.6 1760.79  5652.3 1761.65
  5811.7 1761.90  5816.7 1761.42  5899.7 1761.80  5904.7 1762.52  6076.8 1763.43
#Mann=3,-1,0
  4249.1    0.05       0  4991.7    0.05       0  4995.7    0.05       0
Bank Sta=4991.7,4995.7
Exp/Cntr=0.3,0.1

Type RM Length L Ch R = 1,4765,303,303,303
BEGIN DESCRIPTION:
Mapping XS 78ed68cc
END DESCRIPTION:
XS GIS Cut Line= 4
      1604417.94      6829307.78      1604613.27      6829719.26
      1604764.31      6830440.62      1604923.14      6830753.07
#Sta/Elev= 30
  4310.8 1759.41  4377.5 1758.41  4458.0 1758.44  4565.6 1756.46  4668.1 1756.43
  4698.5 1757.82  4799.9 1757.81  4805.9 1756.69  4816.1 1756.10  4826.3 1756.64
  4899.8 1756.04  4908.0 1754.87  4938.7 1753.86  4959.1 1752.15  4979.6 1751.82
  4994.6 1749.47  4998.0 1747.97  4998.2 1747.47  5001.7 1747.47  5002.0 1747.97
  5020.4 1748.67  5030.6 1749.85  5089.4 1752.18  5122.6 1752.53  5275.8 1756.66
  5357.6 1757.56  5389.0 1758.63  5510.9 1758.91  5567.7 1760.04  5853.8 1761.70
#Mann=3,-1,0
  4310.8    0.05       0  4998.0    0.05       0  5002.0    0.05       0
Bank Sta=4998,5002
Exp/Cntr=0.3,0.1

Type RM Length L Ch R = 1,4462,152,152,152
BEGIN DESCRIPTION:
Mapping XS 4eb50857
END DESCRIPTION:
XS GIS Cut Line= 4
      1604074.20      6829568.21      1604264.31      6829911.97
      1604566.40      6830255.72      1604686.20      6830451.06
#Sta/Elev= 30
  4385.0 1756.94  4510.5 1755.55  4524.3 1755.56  4540.3 1756.64  4590.4 1755.07
  4621.6 1756.04  4627.4 1755.41  4636.2 1755.87  4670.9 1754.96  4730.4 1755.98
  4752.2 1754.15  4803.7 1753.36  4811.3 1753.99  4817.9 1753.24  4846.4 1753.52
  4881.5 1752.72  4945.6 1750.01  4966.9 1748.28  4981.1 1748.32  4985.8 1746.67
  4986.0 1746.17  4989.8 1746.67  5002.0 1748.18  5044.7 1749.61  5079.8 1752.29
  5122.5 1752.09  5200.3 1754.74  5249.9 1755.23  5301.2 1756.86  5464.6 1758.74
#Mann=3,-1,0
  4385.0    0.05       0  4985.8    0.05       0  4989.8    0.05       0
Bank Sta=4985.8,4989.8
Exp/Cntr=0.3,0.1

Type RM Length L Ch R = 1,4310,95,95,95
BEGIN DESCRIPTION:
Elm 02 04 4310.188
END DESCRIPTION:
XS GIS Cut Line= 3
      1604104.99      6829887.99      1604286.82      6830157.12
      1604604.99      6830437.99
#Sta/Elev= 30
  4675.2 1757.34  4688.7 1756.61  4711.4 1756.71  4747.6 1755.49  4769.6 1755.65
  4841.5 1753.26  4856.2 1753.47  4862.5 1752.65  4892.4 1751.93  4934.5 1750.25
  4949.4 1749.12  4970.4 1748.50  4985.4 1747.11  4989.4 1746.16  4989.7 1745.66
  4993.2 1745.66  4993.4 1746.16  4997.5 1747.15  5055.9 1749.29  5063.5 1750.44
  5070.1 1750.80  5098.6 1750.73  5127.0 1752.12  5141.2 1751.70  5169.7 1752.24
  5233.3 1754.52  5311.1 1755.67  5339.5 1757.00  5374.6 1756.93  5424.4 1757.53
#Mann=3,-1,0
  4675.2    0.05       0  4989.4    0.05       0  4993.4    0.05       0
Bank Sta=4989.4,4993.4
Exp/Cntr=0.3,0.1

Type RM Length L Ch R = 1,4215,323,323,323
BEGIN DESCRIPTION:
Mapping XS 905558db
END DESCRIPTION:
XS GIS Cut Line= 4
      1604073.57      6829963.20      1604149.51      6830067.35
      1604264.53      6830325.60      1604409.95      6830573.03
#Sta/Elev= 30
  4700.7 1755.67  4733.1 1756.02  4741.6 1755.45  4833.3 1753.23  4851.1 1752.61
  4856.5 1751.66  4863.2 1751.26  4874.1 1751.05  4885.2 1751.49  4908.5 1749.56
  4931.7 1748.43  4949.5 1747.02  4955.0 1747.18  4972.6 1746.48  4978.2 1746.55
  4983.7 1747.28  4992.5 1746.01  4992.8 1745.51  4996.3 1745.51  4996.5 1746.01
  5001.4 1747.48  5016.4 1748.26  5024.7 1748.14  5030.1 1749.22  5071.1 1749.62
  5122.0 1750.94  5143.5 1751.91  5196.3 1752.56  5362.2 1756.59  5399.3 1756.95
#Mann=3,-1,0
  4700.7    0.05       0  4992.5    0.05       0  4996.5    0.05       0
Bank Sta=4992.5,4996.5
Exp/Cntr=0.3,0.1

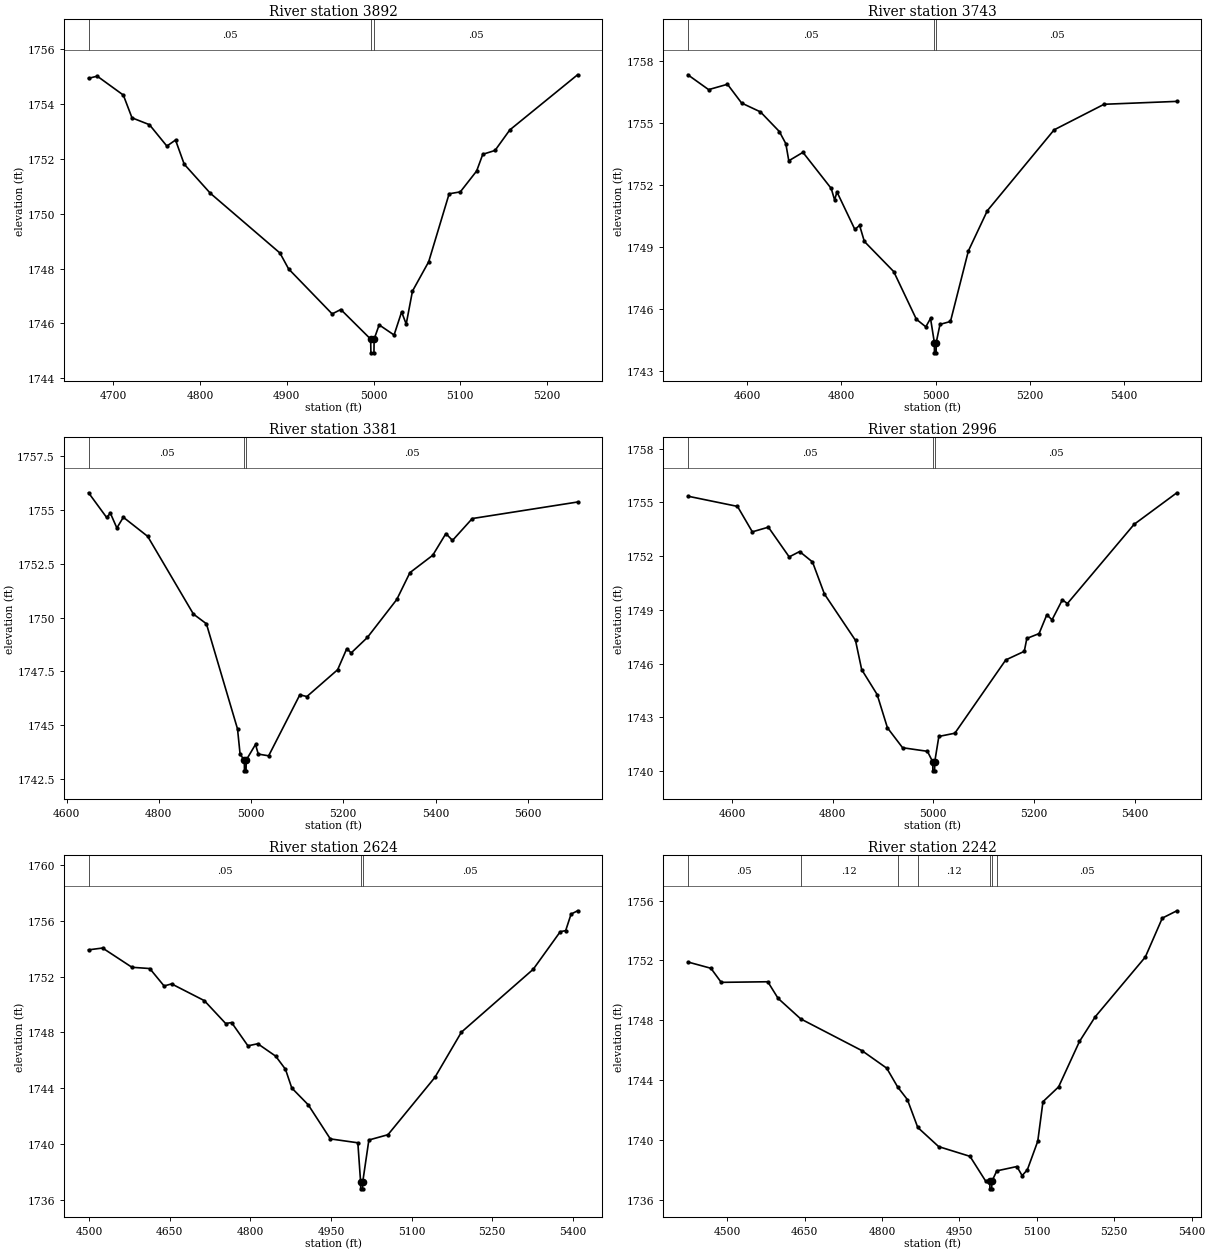
Type RM Length L Ch R = 1,3892,149,149,149
BEGIN DESCRIPTION:
Elm 02 04 3892.031
END DESCRIPTION:
XS GIS Cut Line= 3
      1604005.00      6830038.03      1603978.36      6830365.55
      1604055.01      6830588.02
#Sta/Elev= 30
  4671.4 1754.94  4681.4 1755.02  4711.5 1754.33  4721.5 1753.50  4741.6 1753.25
  4761.7 1752.47  4771.7 1752.69  4781.7 1751.81  4811.8 1750.75  4892.1 1748.57
  4902.1 1747.99  4952.3 1746.35  4962.3 1746.51  4996.7 1745.43  4997.0 1744.93
  5000.5 1744.93  5000.7 1745.43  5006.5 1745.95  5023.7 1745.58  5032.4 1746.42
  5037.7 1745.98  5044.9 1747.18  5063.6 1748.25  5087.2 1750.73  5100.1 1750.80
  5118.9 1751.56  5126.0 1752.17  5140.1 1752.31  5157.2 1753.06  5235.3 1755.07
#Mann=3,-1,0
  4671.4    0.05       0  4996.7    0.05       0  5000.7    0.05       0
Bank Sta=4996.7,5000.7
Exp/Cntr=0.3,0.1

Type RM Length L Ch R = 1,3743,362,362,362
BEGIN DESCRIPTION:
Mapping XS c60f6aa9
END DESCRIPTION:
XS GIS Cut Line= 4
      1603834.63      6829813.90      1603828.12      6830104.68
      1603867.18      6830573.43      1604058.14      6830773.08
#Sta/Elev= 30
  4474.4 1757.34  4518.5 1756.62  4558.5 1756.88  4588.5 1755.97  4628.5 1755.54
  4668.5 1754.59  4682.3 1754.00  4688.6 1753.17  4718.6 1753.58  4778.6 1751.83
  4785.8 1751.27  4790.8 1751.66  4828.8 1749.84  4838.8 1750.04  4848.9 1749.26
  4911.2 1747.80  4959.2 1745.49  4979.3 1745.12  4989.3 1745.53  4997.4 1744.36
  4997.6 1743.86  5001.1 1743.86  5001.4 1744.36  5009.4 1745.24  5031.6 1745.38
  5069.6 1748.80  5109.8 1750.75  5251.5 1754.67  5357.5 1755.91  5511.9 1756.05
#Mann=3,-1,0
  4474.4    0.05       0  4997.4    0.05       0  5001.4    0.05       0
Bank Sta=4997.4,5001.4
Exp/Cntr=0.3,0.1

Type RM Length L Ch R = 1,3381,385,385,385
BEGIN DESCRIPTION:
Mapping XS cef62c8f
END DESCRIPTION:
XS GIS Cut Line= 3
      1603368.07      6829952.81      1603615.44      6830458.41
      1603995.25      6830779.62
#Sta/Elev= 30
  4647.7 1755.81  4686.9 1754.66  4695.0 1754.86  4709.1 1754.17  4723.1 1754.67
  4775.9 1753.78  4875.1 1750.16  4903.2 1749.71  4970.7 1744.81  4976.3 1743.63
  4985.5 1743.36  4985.7 1742.86  4989.2 1742.86  4989.5 1743.36  5009.7 1744.09
  5015.7 1743.64  5038.2 1743.56  5105.8 1746.40  5121.1 1746.32  5187.8 1747.57
  5207.6 1748.55  5217.1 1748.35  5252.2 1749.07  5316.0 1750.84  5344.5 1752.09
  5394.0 1752.90  5422.5 1753.91  5436.8 1753.59  5479.7 1754.61  5708.0 1755.38
#Mann=3,-1,0
  4647.7    0.05       0  4985.5    0.05       0  4989.5    0.05       0
Bank Sta=4985.5,4989.5
Exp/Cntr=0.3,0.1

Type RM Length L Ch R = 1,2996,372,372,372
BEGIN DESCRIPTION:
Mapping XS aa5fbb56
END DESCRIPTION:
XS GIS Cut Line= 4
      1603155.38      6830063.48      1603226.99      6830328.21
      1603315.96      6830742.70      1603370.10      6831011.22
#Sta/Elev= 30
  4512.0 1755.34  4610.7 1754.77  4640.2 1753.35  4672.1 1753.61  4713.5 1751.95
  4734.2 1752.25  4759.8 1751.67  4783.5 1749.88  4845.3 1747.29  4857.6 1745.66
  4888.3 1744.27  4908.8 1742.41  4938.9 1741.30  4988.3 1741.10  4998.8 1740.51
  4999.1 1740.01  5002.6 1740.01  5002.8 1740.51  5011.0 1741.93  5042.8 1742.11
  5144.0 1746.20  5180.8 1746.68  5185.9 1747.40  5210.2 1747.67  5225.6 1748.72
  5236.0 1748.44  5256.4 1749.55  5266.6 1749.35  5399.2 1753.77  5484.1 1755.53
#Mann=3,-1,0
  4512.0    0.05       0  4998.8    0.05       0  5002.8    0.05       0
Bank Sta=4998.8,5002.8
Exp/Cntr=0.3,0.1

Type RM Length L Ch R = 1,2624,382,382,382
BEGIN DESCRIPTION:
Mapping XS b9d96407
END DESCRIPTION:
XS GIS Cut Line= 4
      1602905.80      6830145.90      1602964.40      6830484.46
      1603053.38      6830890.27      1603066.40      6831040.06
#Sta/Elev= 30
  4499.3 1753.92  4525.4 1754.05  4580.0 1752.67  4613.1 1752.58  4639.8 1751.33
  4653.7 1751.48  4714.6 1750.28  4754.3 1748.64  4765.3 1748.71  4795.7 1747.04
  4814.0 1747.19  4847.3 1746.30  4865.5 1745.36  4877.2 1744.02  4907.9 1742.81
  4948.9 1740.37  5000.1 1740.09  5005.2 1737.29  5005.4 1736.79  5008.9 1736.79
  5009.2 1737.29  5020.6 1740.29  5056.1 1740.67  5143.4 1744.78  5192.7 1748.02
  5326.3 1752.53  5376.5 1755.22  5386.6 1755.30  5396.6 1756.48  5408.7 1756.72
#Mann=3,-1,0
  4499.3    0.05       0  5005.2    0.05       0  5009.2    0.05       0
Bank Sta=5005.2,5009.2
Exp/Cntr=0.3,0.1

Type RM Length L Ch R = 1,2242,224,224,224
BEGIN DESCRIPTION:
Mapping XS 86cf266a
END DESCRIPTION:
XS GIS Cut Line= 4
      1602610.67      6830113.38      1602634.54      6830525.69
      1602693.13      6830935.84      1602727.86      6831050.89
#Sta/Elev= 30
  4423.7 1751.90  4468.4 1751.48  4488.4 1750.54  4578.6 1750.58  4598.6 1749.47
  4642.4 1748.10  4761.0 1745.98  4809.0 1744.81  4830.3 1743.55  4849.1 1742.71
  4869.2 1740.85  4909.7 1739.57  4970.4 1738.92  5000.7 1737.27  5008.8 1737.25
  5009.0 1736.75  5012.5 1736.75  5012.8 1737.25  5022.3 1737.95  5061.3 1738.24
  5071.4 1737.63  5081.5 1738.02  5101.7 1739.93  5111.8 1742.57  5142.1 1743.56
  5182.5 1746.59  5212.8 1748.23  5310.1 1752.23  5343.0 1754.83  5371.2 1755.32
#Mann=7,-1,0
  4423.7    0.05       0  4642.4    0.12       0  4830.3    0.05       0
  4869.2    0.12       0  5008.8    0.07       0  5012.8    0.12       0
  5022.3    0.05       0
Bank Sta=5008.8,5012.8
Exp/Cntr=0.3,0.1

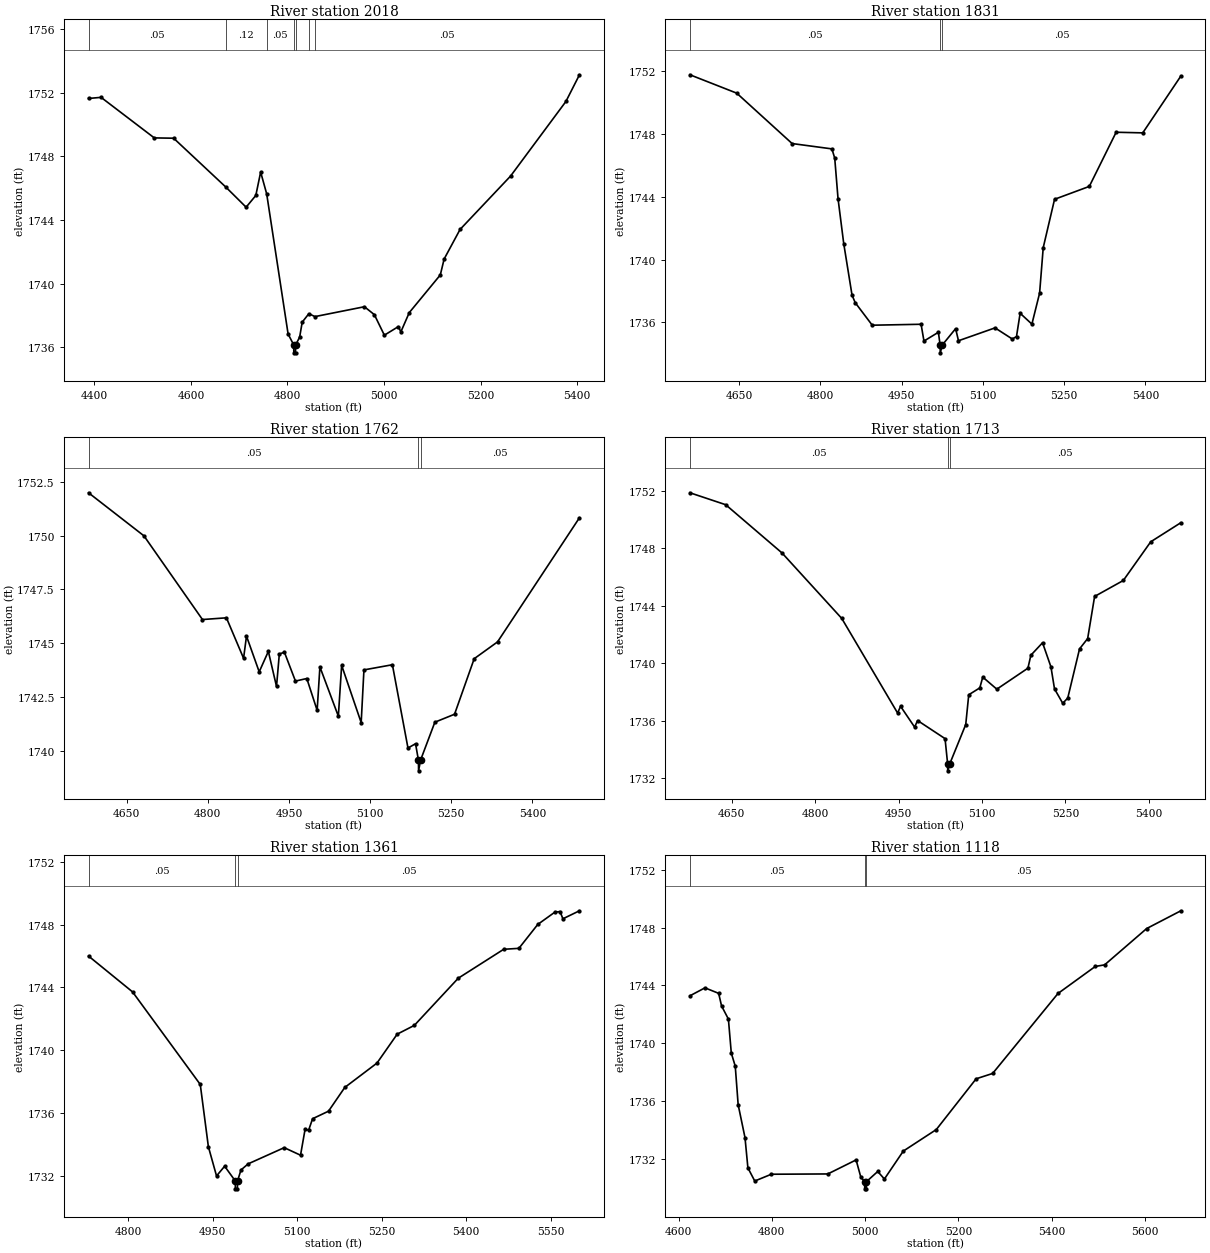
Type RM Length L Ch R = 1,2018,187,187,187
BEGIN DESCRIPTION:
Mapping XS 1e40c4bc
END DESCRIPTION:
XS GIS Cut Line= 4
      1602387.14      6830072.09      1602413.18      6830486.63
      1602521.69      6830911.97      1602619.36      6831042.20
#Sta/Elev= 30
  4387.9 1751.65  4413.9 1751.72  4524.1 1749.17  4564.2 1749.15  4672.2 1746.08
  4714.4 1744.81  4734.5 1745.55  4744.5 1747.02  4757.0 1745.65  4801.4 1736.83
  4813.0 1736.15  4813.2 1735.65  4816.7 1735.65  4817.0 1736.15  4825.3 1736.64
  4830.6 1737.58  4844.3 1738.11  4857.1 1737.93  4959.5 1738.55  4980.1 1738.05
  5000.8 1736.76  5029.8 1737.30  5035.0 1736.97  5052.4 1738.18  5116.7 1740.55
  5124.6 1741.55  5157.6 1743.41  5262.3 1746.77  5376.9 1751.46  5405.0 1753.14
#Mann=7,-1,0
  4387.9    0.05       0  4672.2    0.12       0  4757.0    0.05       0
  4813.0    0.03       0  4817.0    0.05       0  4844.3    0.12       0
  4857.1    0.05       0
Bank Sta=4813,4817
Exp/Cntr=0.3,0.1

Type RM Length L Ch R = 1,1831,69,69,69
BEGIN DESCRIPTION:
Mapping XS cdd30c0a
END DESCRIPTION:
XS GIS Cut Line= 6
      1602141.93      6830250.12      1602226.55      6830490.97
      1602328.55      6830816.49      1602424.04      6830901.12
      1602497.82      6830974.91      1602540.62      6831039.11
#Sta/Elev= 30
  4559.7 1751.77  4646.0 1750.60  4748.2 1747.39  4821.6 1747.05  4826.8 1746.46
  4832.9 1743.88  4843.4 1741.02  4858.7 1737.74  4864.5 1737.26  4896.0 1735.82
  4986.1 1735.88  4991.4 1734.81  5018.0 1735.37  5021.2 1734.56  5021.5 1734.06
  5025.2 1734.56  5049.8 1735.60  5055.1 1734.83  5122.5 1735.65  5154.4 1734.94
  5162.1 1735.10  5168.8 1736.58  5190.5 1735.89  5204.7 1737.86  5211.4 1740.76
  5232.3 1743.84  5296.4 1744.66  5345.9 1748.11  5395.0 1748.07  5465.3 1751.69
#Mann=3,-1,0
  4559.7    0.05       0  5021.2    0.05       0  5025.2    0.05       0
Bank Sta=5021.2,5025.2
Exp/Cntr=0.3,0.1

Type RM Length L Ch R = 1,1762,49,49,49
BEGIN DESCRIPTION:
Mapping XS 0254d451
END DESCRIPTION:
XS GIS Cut Line= 6
      1602074.65      6830273.97      1602204.85      6830575.60
      1602263.45      6830801.30      1602296.00      6830855.55
      1602476.12      6830990.10      1602504.32      6831039.99
#Sta/Elev= 30
  4579.4 1751.99  4681.8 1749.99  4790.0 1746.10  4834.3 1746.18  4866.0 1744.30
  4871.4 1745.33  4894.9 1743.67  4911.8 1744.62  4926.9 1742.99  4932.1 1744.50
  4941.5 1744.58  4961.9 1743.24  4982.9 1743.36  5002.0 1741.88  5007.1 1743.90
  5041.2 1741.61  5047.3 1743.97  5083.4 1741.31  5088.5 1743.76  5141.1 1744.00
  5169.9 1740.13  5183.9 1740.33  5189.2 1739.57  5189.5 1739.07  5193.2 1739.57
  5219.6 1741.33  5256.0 1741.70  5292.3 1744.28  5335.4 1745.06  5486.9 1750.83
#Mann=3,-1,0
  4579.4    0.05       0  5189.2    0.05       0  5193.2    0.05       0
Bank Sta=5189.2,5193.2
Exp/Cntr=0.3,0.1

Type RM Length L Ch R = 1,1713,352,352,352
BEGIN DESCRIPTION:
Mapping XS d2c7678e
END DESCRIPTION:
XS GIS Cut Line= 5
      1602009.56      6830300.03      1602152.77      6830595.13
      1602250.42      6830864.23      1602374.12      6830944.52
      1602456.34      6831033.23
#Sta/Elev= 30
  4574.8 1751.85  4639.1 1751.02  4740.5 1747.66  4847.8 1743.11  4948.2 1736.53
  4953.5 1737.00  4978.8 1735.55  4984.1 1736.01  5033.5 1734.75  5038.1 1733.01
  5038.3 1732.51  5042.1 1733.01  5070.7 1735.73  5076.1 1737.80  5096.0 1738.28
  5101.3 1739.03  5126.6 1738.19  5182.5 1739.65  5187.8 1740.55  5208.8 1741.42
  5223.9 1739.74  5230.3 1738.21  5245.1 1737.21  5254.1 1737.57  5275.3 1740.99
  5289.9 1741.71  5302.4 1744.64  5354.0 1745.75  5403.3 1748.44  5457.5 1749.77
#Mann=3,-1,0
  4574.8    0.05       0  5038.1    0.05       0  5042.1    0.05       0
Bank Sta=5038.1,5042.1
Exp/Cntr=0.3,0.1

Type RM Length L Ch R = 1,1361,243,243,243
BEGIN DESCRIPTION:
Mapping XS ce696710
END DESCRIPTION:
XS GIS Cut Line= 3
      1601681.86      6830632.04      1602135.41      6830987.93
      1602428.41      6831026.99
#Sta/Elev= 30
  4729.2 1746.00  4807.4 1743.72  4927.7 1737.83  4942.1 1733.87  4956.6 1732.01
  4971.0 1732.63  4989.9 1731.69  4990.1 1731.19  4993.6 1731.19  4993.9 1731.69
  5000.0 1732.39  5012.8 1732.78  5076.8 1733.81  5105.8 1733.33  5113.9 1734.98
  5120.2 1734.92  5127.2 1735.65  5155.5 1736.13  5184.4 1737.64  5241.6 1739.19
  5277.5 1741.03  5308.0 1741.59  5386.0 1744.59  5466.7 1746.43  5493.7 1746.49
  5527.2 1748.01  5557.5 1748.79  5566.8 1748.83  5571.9 1748.37  5601.3 1748.88
#Mann=3,-1,0
  4729.2    0.05       0  4989.9    0.05       0  4993.9    0.05       0
Bank Sta=4989.9,4993.9
Exp/Cntr=0.3,0.1

Type RM Length L Ch R = 1,1118,321,321,321
BEGIN DESCRIPTION:
Mapping XS 664ba393
END DESCRIPTION:
XS GIS Cut Line= 4
      1601414.95      6830853.40      1601562.49      6830959.72
      1601976.99      6831022.65      1602428.40      6831035.67
#Sta/Elev= 30
  4624.5 1743.28  4656.7 1743.83  4686.1 1743.45  4692.3 1742.58  4707.0 1741.67
  4713.2 1739.32  4721.7 1738.41  4727.9 1735.75  4742.6 1733.47  4748.8 1731.38
  4763.5 1730.47  4799.1 1730.94  4920.2 1730.96  4980.8 1731.93  4991.0 1730.73
  4999.1 1730.43  4999.3 1729.93  5002.8 1729.93  5003.1 1730.43  5027.2 1731.13
  5041.5 1730.61  5082.0 1732.54  5152.8 1734.03  5238.2 1737.54  5273.6 1737.91
  5413.7 1743.44  5493.7 1745.31  5513.7 1745.42  5603.8 1747.93  5677.2 1749.16
#Mann=3,-1,0
  4624.5    0.05       0  4999.1    0.05       0  5003.1    0.05       0
Bank Sta=4999.1,5003.1
Exp/Cntr=0.3,0.1

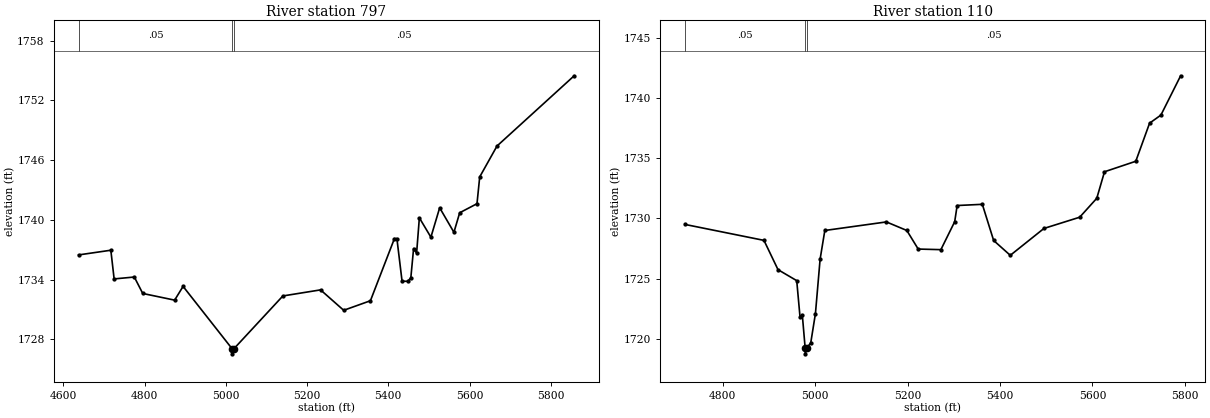
Type RM Length L Ch R = 1,797,687,687,687
BEGIN DESCRIPTION:
Mapping XS 97100f28
END DESCRIPTION:
XS GIS Cut Line= 4
      1601351.97      6830979.23      1601542.96      6831220.13
      1601933.58      6831484.89      1602259.12      6831782.21
#Sta/Elev= 30
  4637.5 1736.49  4716.8 1736.96  4724.9 1734.08  4774.6 1734.27  4795.4 1732.62
  4873.9 1731.95  4894.7 1733.33  5015.6 1727.06  5015.8 1726.56  5019.6 1727.06
  5140.4 1732.37  5233.2 1732.98  5290.2 1730.93  5356.0 1731.89  5415.1 1738.13
  5421.2 1738.13  5433.9 1733.85  5448.1 1733.84  5455.5 1734.20  5462.3 1737.13
  5469.7 1736.66  5476.5 1740.21  5504.9 1738.27  5526.5 1741.22  5561.6 1738.76
  5575.8 1740.72  5618.4 1741.63  5625.1 1744.32  5667.7 1747.42  5857.7 1754.47
#Mann=3,-1,0
  4637.5    0.05       0  5015.6    0.03       0  5019.6    0.05       0
Bank Sta=5015.6,5019.6
Exp/Cntr=0.3,0.1

Type RM Length L Ch R = 1,110,0,0,0
BEGIN DESCRIPTION:
Elm 02 04 547.517
END DESCRIPTION:
XS GIS Cut Line= 3
      1601069.87      6831059.53      1601134.97      6831461.02
      1601375.86      6832081.68
#Sta/Elev= 30
  4718.3 1729.50  4889.0 1728.18  4919.4 1725.75  4959.9 1724.84  4967.0 1721.84
  4972.1 1721.95  4978.1 1719.27  4978.4 1718.77  4982.1 1719.27  4990.3 1719.69
  5000.4 1722.11  5010.5 1726.62  5020.7 1729.00  5154.0 1729.71  5198.2 1729.00
  5222.8 1727.46  5271.9 1727.41  5301.8 1729.73  5307.1 1731.07  5361.6 1731.17
  5386.1 1728.17  5422.1 1726.94  5495.0 1729.17  5572.3 1730.10  5609.3 1731.67
  5626.0 1733.87  5693.7 1734.74  5723.6 1737.90  5748.1 1738.57  5790.8 1741.83
#Mann=3,-1,0
  4718.3    0.05       0  4978.1    0.03       0  4982.1    0.05       0
Bank Sta=4978.1,4982.1
Exp/Cntr=0.3,0.1

Chan Stop Cuts=-1