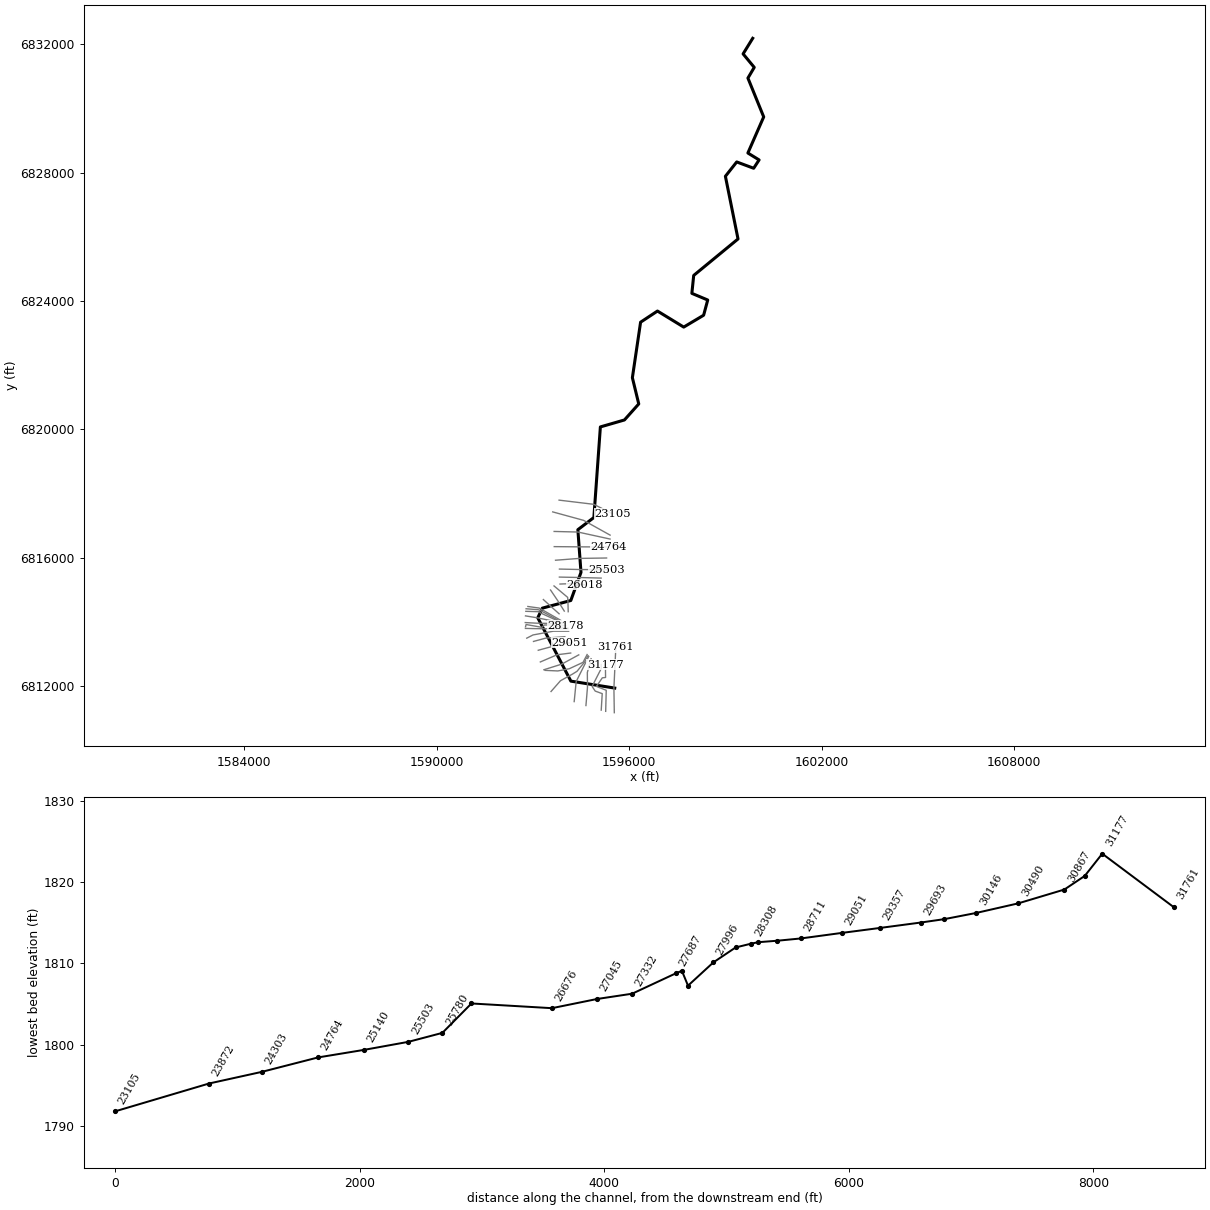
--- Elm 02 05.prj (project) ---

Proj Title=Elm 02 05 Base Level Engineering
Current Plan=p01
Default Exp/Contr=0.3,0.1
English Units
Geom File=g01
Flow File=f01
Plan File=p01
Y Axis Title=Elevation
X Axis Title(PF)=Main Channel Distance
X Axis Title(XS)=Station
BEGIN DESCRIPTION:
Elm 02 05
END DESCRIPTION:
DSS Export Rating Curves= 0
DSS Export Rating Curve Sorted= 0
DSS Export Volume Flow Curves= 0
DXF OffsetX= 0
DXF OffsetY= 0
DXF ScaleX= 1
DXF ScaleY= 10

--- Elm 02 05.p01 (plan) ---

Plan Title=Multiple Run
Short Identifier=Multiple
Geom File=g01
Flow File=f01
Subcritical Flow
K Sum by GR= 0
Std Step Tol= 0.01
Critical Tol= 0.01
Num of Std Step Trials= 20
Max Error Tol= 0.3
Flow Tol Ratio= 0.001
Split Flow NTrial= 30
Split Flow Tol= 0.02
Split Flow Ratio= 0.02
Log Output Level= 0
Friction Slope Method= 1
Unsteady Friction Slope Method= 2
Unsteady Bridges Friction Slope Method= 1
Parabolic Critical Depth
Global Vel Dist=  1 , 1 , 1
Global Log Level= 0
CheckData=True
Encroach Param= -1, 0, 0, 0
BEGIN DESCRIPTION:
Multiple Run
END DESCRIPTION:

--- Elm 02 05.f01 (steady flow) ---

Flow Title=Multiple
Number of Profiles=7
Profile Names=10-year,25-year,50-year,1pct_min,100-year,1pct_plu,500-year
River Rch & RM= Elm 02 05,Reach-1,31761
     159     211     253     187     300     413     429
River Rch & RM= Elm 02 05,Reach-1,30867
     288     398     488     370     593     816     889
River Rch & RM= Elm 02 05,Reach-1,21079
     371     519     642     491     787    1080    1200
River Rch & RM= Elm 02 05,Reach-1,13950
     605     866    1090     843    1350    1860    2120
Boundary for River Rch & Prof#=Elm 02 05,Reach-1,1
Up Type=0
Dn Type=3
Dn Slope=0.001
Boundary for River Rch & Prof#=Elm 02 05,Reach-1,2
Up Type=0
Dn Type=3
Dn Slope=0.001
Boundary for River Rch & Prof#=Elm 02 05,Reach-1,3
Up Type=0
Dn Type=3
Dn Slope=0.001
Boundary for River Rch & Prof#=Elm 02 05,Reach-1,4
Up Type=0
Dn Type=3
Dn Slope=0.001
Boundary for River Rch & Prof#=Elm 02 05,Reach-1,5
Up Type=0
Dn Type=3
Dn Slope=0.001
Boundary for River Rch & Prof#=Elm 02 05,Reach-1,6
Up Type=0
Dn Type=3
Dn Slope=0.001
Boundary for River Rch & Prof#=Elm 02 05,Reach-1,7
Up Type=0
Dn Type=3
Dn Slope=0.001

--- Elm 02 05.g01 (geometry) ---

Geom Title=Existing Conditions
Program Version=4.10

River Reach=Elm 02 05       ,Reach-1
Reach XY= 30
        1595555.        6811938.       1594188.2      6812154.42
      1593155.93      6814128.15      1593298.25      6814428.86
      1594185.57      6814667.34      1594502.65      6815543.52
      1594405.68      6816874.08      1594904.46      6817253.54
      1595107.15      6820076.73       1595857.3      6820293.83
      1596303.38      6820793.46      1596104.63      6821610.88
      1596360.46      6823340.45      1596886.66      6823687.96
        1597705.        6823188.       1598325.2      6823557.56
      1598452.95      6824032.14      1597958.53      6824239.44
      1598015.95        6824798.      1599397.21      6825934.57
      1599003.96      6827887.67      1599356.63      6828334.88
      1599884.94      6828137.78      1600054.14      6828397.92
      1599704.45      6828612.88      1600197.77      6829738.31
      1599705.93      6830948.48      1599902.96      6831282.13
      1599555.68      6831701.92        1599855.        6832188.

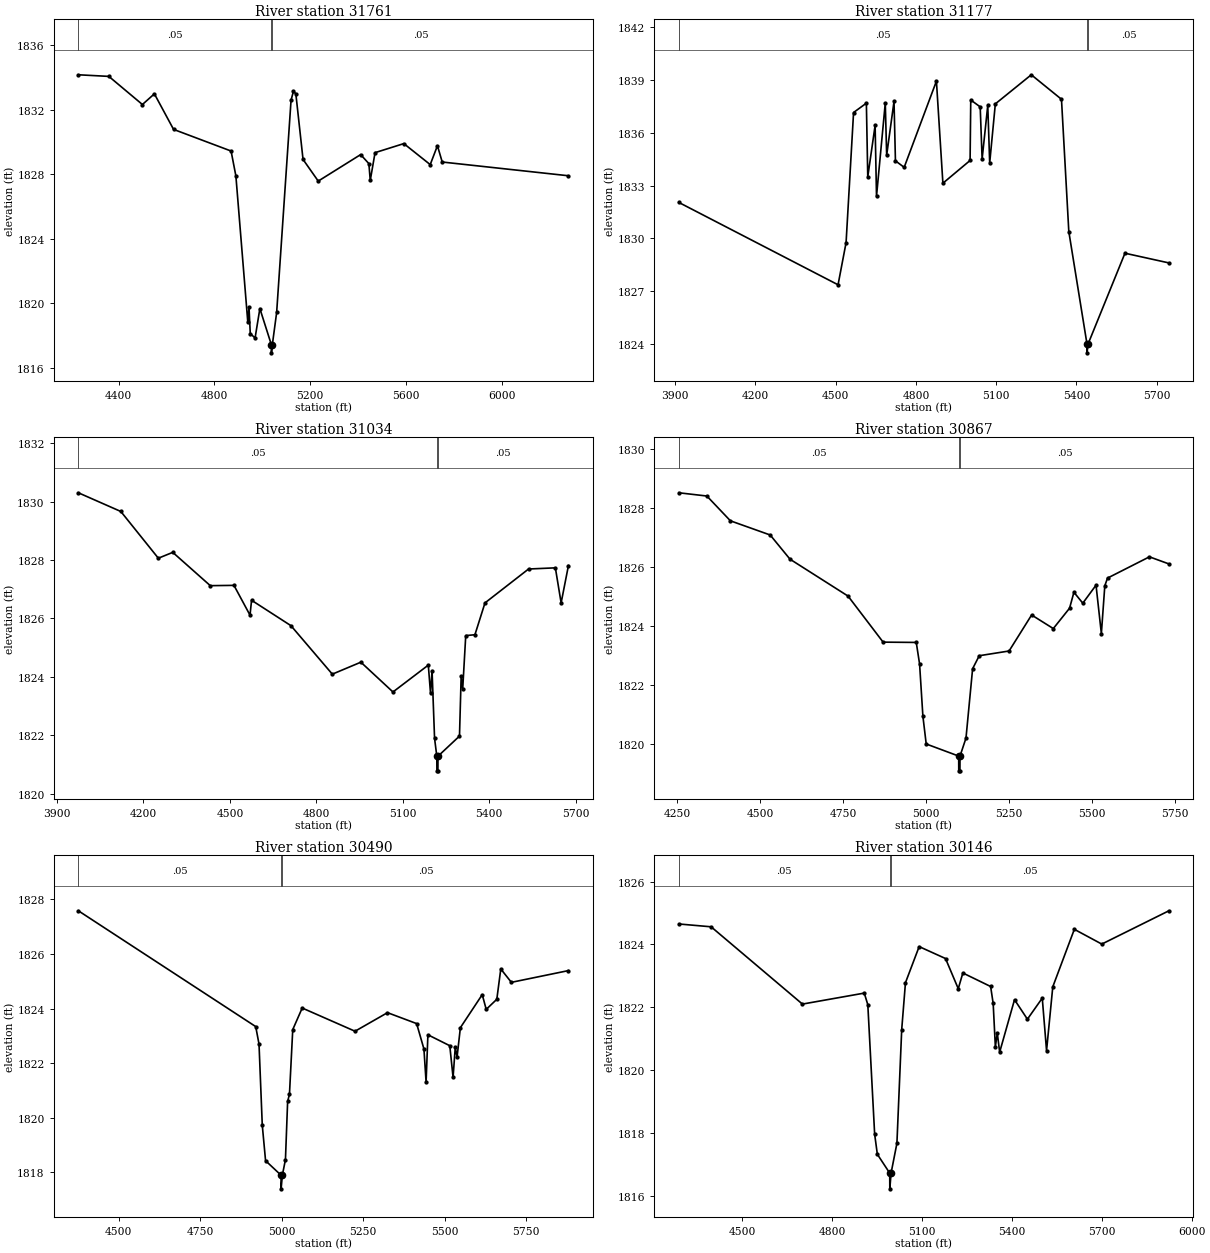
Type RM Length L Ch R = 1 ,31761   ,584,584,584
BEGIN DESCRIPTION:
Elm 02 05 31402.783
END DESCRIPTION:
XS GIS Cut Line= 3
      1595541.54      6811170.85       1595529.1      6811938.25
      1595589.23      6813214.03
#Sta/Elev= 30
  4232.5 1834.15  4359.7 1834.05  4499.7 1832.31  4549.7 1832.97  4629.7 1830.77
  4869.7 1829.43  4889.7 1827.89  4939.5 1818.83  4944.5 1819.76  4949.7 1818.13
  4969.8 1817.86  4989.8 1819.68  5037.8 1817.44    5038 1816.94  5041.8 1817.44
  5059.8 1819.44  5119.9 1832.58  5129.9 1833.13  5139.9 1832.97  5169.9 1828.91
  5233.3 1827.57  5410.2 1829.21  5444.6 1828.65  5450.3 1827.61  5470.3 1829.33
  5590.4 1829.89  5700.5 1828.59  5730.6 1829.76  5750.6 1828.75  6277.2  1827.9
#Mann= 3 ,-1 , 0
  4232.5     .05       0  5037.8     .05       0  5041.8     .05       0
Bank Sta=5037.8,5041.8
XS Rating Curve= 0 ,0
Exp/Cntr=0.3,0.1

Type RM Length L Ch R = 1 ,31177   ,143,143,143
BEGIN DESCRIPTION:
Elm 02 05 31177.34
END DESCRIPTION:
XS GIS Cut Line= 6
      1595272.55      6811212.68      1595289.91      6811868.93
      1594984.35      6811990.46      1595168.38      6812257.82
      1595269.07      6812268.24      1595263.56      6812672.41
#Sta/Elev= 30
  3913.3 1832.04  4508.8 1827.37  4538.8 1829.76  4566.8 1837.14  4614.7 1837.67
  4619.9 1833.49  4647.4 1836.41  4652.6 1832.39  4685.4 1837.68  4690.6 1834.72
  4718.1 1837.77  4723.4  1834.4  4756.1 1834.03  4876.7 1838.92  4900.9 1833.13
  5002.6 1834.42  5005.1 1837.85  5040.4 1837.46  5047.6 1834.51  5068.7 1837.54
  5075.9 1834.28    5097 1837.63  5231.5 1839.28  5344.4 1837.89  5371.8 1830.39
  5439.8 1824.01    5440 1823.51  5443.8 1824.01  5581.8 1829.16  5746.2 1828.61
#Mann= 3 ,-1 , 0
  3913.3     .05       0  5439.8     .04       0  5443.8     .05       0
Bank Sta=5439.8,5443.8
XS Rating Curve= 0 ,0
Exp/Cntr=0.3,0.1

Type RM Length L Ch R = 1 ,31034   ,167,167,167
BEGIN DESCRIPTION:
Elm 02 05 31034.22
END DESCRIPTION:
XS GIS Cut Line= 6
      1595133.66       6811250.9      1595164.91      6811764.77
      1594946.16      6811844.63      1594848.94      6811990.46
      1595133.66      6812546.02      1595132.02      6812673.38
#Sta/Elev= 30
    3974  1830.3  4121.4 1829.66  4251.6 1828.06  4301.7 1828.26  4431.9 1827.12
  4514.1 1827.13  4569.8 1826.11  4575.2 1826.62  4711.9 1825.75  4855.5 1824.09
  4954.6  1824.5    5066 1823.48  5188.7  1824.4  5196.3 1823.44  5201.7 1824.21
  5210.4 1821.89  5218.2 1821.28  5218.5 1820.78    5222 1820.78  5222.2 1821.28
  5296.9 1821.97  5302.7 1824.01  5308.1 1823.59  5318.6 1825.41  5350.5 1825.44
  5385.4 1826.53  5536.6 1827.69  5629.7 1827.73  5649.7 1826.53  5675.1 1827.81
#Mann= 3 ,-1 , 0
    3974     .05       0  5218.2     .07       0  5222.2     .05       0
Bank Sta=5218.2,5222.2
XS Rating Curve= 0 ,0
Exp/Cntr=0.3,0.1

Type RM Length L Ch R = 1 ,30867   ,377,377,377
BEGIN DESCRIPTION:
Mapping XS 8373bbaa
END DESCRIPTION:
XS GIS Cut Line= 4
      1594657.32      6811393.74      1594705.07      6811962.32
      1594700.73      6812422.39      1594817.46      6812854.73
#Sta/Elev= 30
  4254.4 1828.52    4339 1828.41    4410 1827.57    4530 1827.09  4589.8 1826.27
  4764.9 1825.02  4870.7 1823.46  4970.7 1823.45  4980.7 1822.72  4990.7 1820.95
  5000.7 1820.01  5098.7  1819.6  5098.9  1819.1  5102.4  1819.1  5102.7  1819.6
  5120.7 1820.21  5140.7 1822.56  5160.7    1823  5250.7 1823.16  5318.7 1824.38
  5384.1 1823.92  5433.2 1824.61  5446.3 1825.15  5473.1 1824.78    5513 1825.39
  5529.1 1823.75  5539.5 1825.37  5547.7 1825.63  5674.1 1826.35  5732.9 1826.11
#Mann= 3 ,-1 , 0
  4254.4     .05       0  5098.7     .05       0  5102.7     .05       0
Bank Sta=5098.7,5102.7
XS Rating Curve= 0 ,0
Exp/Cntr=0.3,0.1

Type RM Length L Ch R = 1 ,30490   ,344,344,344
BEGIN DESCRIPTION:
Elm 02 05 30489.68
END DESCRIPTION:
XS GIS Cut Line= 3
      1594290.77      6811516.47      1594353.28       6812141.5
      1594744.83      6812924.62
#Sta/Elev= 30
  4376.2 1827.58  4920.4 1823.34  4930.5  1822.7  4940.5 1819.73  4950.6 1818.43
    4998  1817.9  4998.3  1817.4  5002.1  1817.9  5011.6 1818.47  5018.3  1820.6
  5023.9 1820.86    5034 1823.23    5063 1824.02  5225.1 1823.17  5324.7 1823.85
  5414.1 1823.45  5436.5 1822.52  5443.1 1821.31  5448.7 1823.04  5515.8 1822.64
  5525.9 1821.48  5532.6 1822.58  5538.2 1822.23  5548.3  1823.3  5615.4 1824.51
  5627.6 1823.97  5660.1 1824.34  5672.3 1825.45  5704.8 1824.96  5879.9 1825.39
#Mann= 3 ,-1 , 0
  4376.2     .05       0    4998     .05       0  5002.1     .05       0
Bank Sta=4998,5002.1
XS Rating Curve= 0 ,0
Exp/Cntr=0.3,0.1

Type RM Length L Ch R = 1 ,30146   ,260,260,260
BEGIN DESCRIPTION:
Mapping XS a3d7cb28
END DESCRIPTION:
XS GIS Cut Line= 6
      1593569.66      6811831.25      1593863.92      6812167.18
      1594241.53      6812375.51      1594379.55      6812461.45
      1594611.32      6812745.31      1594720.69      6812945.82
#Sta/Elev= 30
  4288.8 1824.65  4396.5 1824.56  4701.2  1822.1  4907.6 1822.45  4919.4 1822.08
  4942.2 1817.96  4951.2 1817.32  4992.5 1816.72  4992.8 1816.22    4997 1816.72
  5016.5 1817.67  5032.5 1821.29    5045 1822.78  5090.7 1823.93  5178.7 1823.55
  5221.2 1822.59  5236.5 1823.09  5329.2 1822.66  5337.7 1822.12    5345 1820.74
  5351.4 1821.18  5359.3 1820.57  5408.9 1822.24  5451.9 1821.62  5501.5 1822.29
  5515.8 1820.62  5536.6 1822.65  5608.5 1824.48  5700.1 1824.01  5924.1 1825.07
#Mann= 3 ,-1 , 0
  4288.8     .05       0  4992.5     .05       0    4997     .05       0
Bank Sta=4992.5,4997
XS Rating Curve= 0 ,0
Exp/Cntr=0.3,0.1

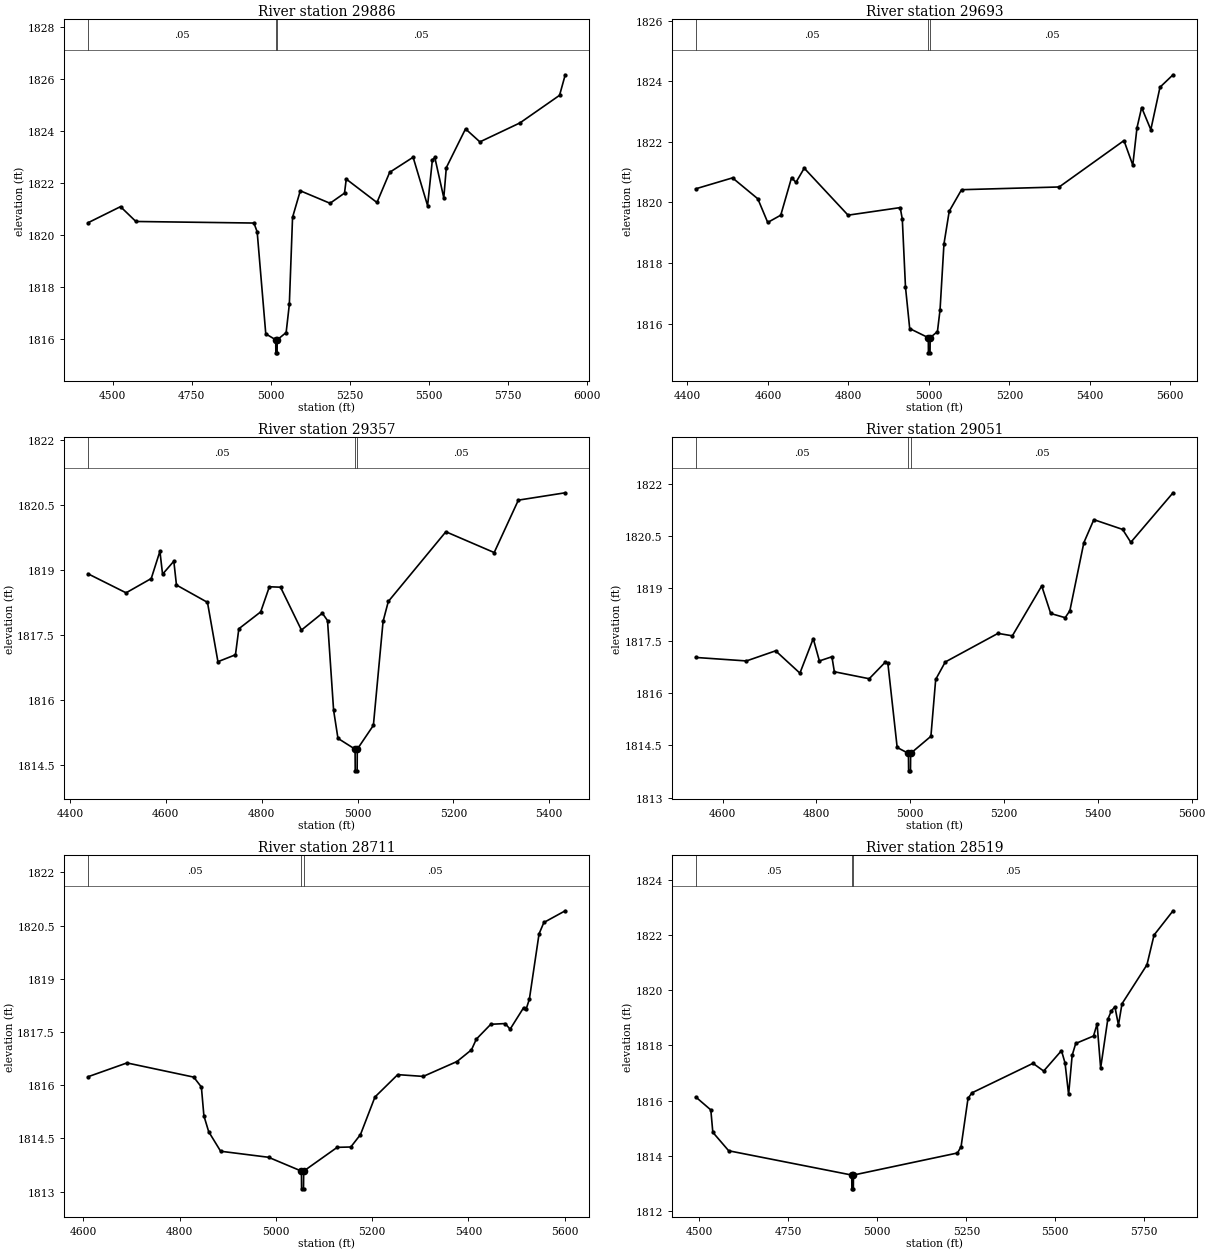
Type RM Length L Ch R = 1 ,29886   ,193,193,193
BEGIN DESCRIPTION:
Mapping XS 22d41b6a
END DESCRIPTION:
XS GIS Cut Line= 5
      1593382.13       6812490.1      1593780.59      6812471.87
      1594134.76      6812539.58      1594567.05       6812740.1
      1594694.17      6812983.96
#Sta/Elev= 30
  4421.6 1820.46  4524.6 1821.08  4573.3 1820.51  4947.1 1820.45  4957.3 1820.11
  4984.5 1816.19  5016.1 1815.96  5016.4 1815.46  5020.4 1815.46  5020.7 1815.96
    5049 1816.24  5059.1 1817.32  5069.3 1820.67  5093.8 1821.69    5188 1821.21
  5233.8  1821.6  5239.3 1822.14  5336.5 1821.24  5376.8  1822.4    5451 1822.98
  5496.8 1821.12    5512 1822.88  5519.7 1822.97  5548.1 1821.42  5556.1 1822.58
  5616.9 1824.07  5662.4 1823.57  5789.3  1824.3  5914.6 1825.36  5932.6 1826.15
#Mann= 3 ,-1 , 0
  4421.6     .05       0  5016.1     .05       0  5020.7     .05       0
Bank Sta=5016.1,5020.7
XS Rating Curve= 0 ,0
Exp/Cntr=0.3,0.1

Type RM Length L Ch R = 1 ,29693   ,336,336,336
BEGIN DESCRIPTION:
Elm 02 05 29692.58
END DESCRIPTION:
XS GIS Cut Line= 3
      1593347.89      6812509.82      1593902.58       6812684.3
      1594433.49      6812973.18
#Sta/Elev= 30
  4420.8 1820.45  4512.1 1820.81    4575 1820.12  4599.6 1819.34    4632 1819.58
  4658.9 1820.82  4669.7 1820.66  4690.3 1821.13  4799.2 1819.58  4928.8 1819.83
    4934 1819.45  4941.9 1817.21  4952.4 1815.84  4998.6 1815.54  4998.9 1815.04
  5002.9 1815.04  5003.2 1815.54  5021.3 1815.74  5027.8 1816.46  5037.5 1818.63
  5050.6 1819.71  5081.2 1820.42  5323.8 1820.51  5484.8 1822.04  5506.7 1821.23
  5517.1 1822.46  5528.7 1823.13  5551.5  1822.4  5574.3  1823.8  5606.7 1824.21
#Mann= 3 ,-1 , 0
  4420.8     .05       0  4998.6    .035       0  5003.2     .05       0
Bank Sta=4998.6,5003.2
XS Rating Curve= 0 ,0
Exp/Cntr=0.3,0.1

Type RM Length L Ch R = 1 ,29357   ,306,306,306
BEGIN DESCRIPTION:
Elm 02 05 29357.3
END DESCRIPTION:
XS GIS Cut Line= 3
      1593235.94      6812752.02      1593756.75      6812975.97
      1594181.96      6813030.41
#Sta/Elev= 30
  4437.7 1818.92  4517.2 1818.48  4569.7 1818.81  4587.8 1819.44  4593.3 1818.91
  4616.8 1819.21  4622.3 1818.66    4687 1818.26  4708.8 1816.89  4745.4 1817.05
  4752.4 1817.65    4798 1818.04  4816.1 1818.62  4839.4 1818.61    4883 1817.62
  4926.6 1818.01  4937.4 1817.84  4950.1 1815.77  4959.2 1815.12  4994.9 1814.87
  4995.2 1814.37  4999.2 1814.37  4999.5 1814.87  5033.1 1815.42  5053.3 1817.82
  5064.2 1818.28  5184.3 1819.89  5285.1 1819.41  5335.5 1820.62  5433.3 1820.79
#Mann= 3 ,-1 , 0
  4437.7     .05       0  4994.9    .035       0  4999.5     .05       0
Bank Sta=4994.9,4999.5
XS Rating Curve= 0 ,0
Exp/Cntr=0.3,0.1

Type RM Length L Ch R = 1 ,29051   ,340,340,340
BEGIN DESCRIPTION:
Elm 02 05 29051.43
END DESCRIPTION:
XS GIS Cut Line= 3
      1593170.77      6813116.58      1593610.91      6813236.38
      1594160.24      6813350.93
#Sta/Elev= 30
    4543 1817.02    4651 1816.92  4713.2 1817.21    4765 1816.57  4793.4 1817.56
  4806.5 1816.92  4833.2 1817.04  4838.4 1816.61  4912.7 1816.41  4947.3 1816.89
  4952.5 1816.85  4972.3 1814.44  4996.3 1814.27  4996.7 1813.77  5000.7 1813.77
    5001 1814.27  5044.2 1814.76  5054.4 1816.39  5074.8 1816.89  5187.2 1817.71
  5217.8 1817.64  5280.4 1819.07  5299.6 1818.28  5330.4 1818.16  5340.4 1818.36
  5370.2 1820.31  5391.5 1820.97  5452.8 1820.69  5470.3 1820.32  5560.3 1821.74
#Mann= 3 ,-1 , 0
    4543     .05       0  4996.3    .035       0    5001     .05       0
Bank Sta=4996.3,5001
XS Rating Curve= 0 ,0
Exp/Cntr=0.3,0.1

Type RM Length L Ch R = 1 ,28711   ,192,192,192
BEGIN DESCRIPTION:
Elm 02 05 28711.28
END DESCRIPTION:
XS GIS Cut Line= 3
      1593022.68      6813391.76      1593402.47      6813493.76
      1593999.28      6813539.34
#Sta/Elev= 30
  4609.6 1816.24  4690.6 1816.63  4829.4 1816.23  4845.3 1815.95  4850.5 1815.14
  4860.5 1814.69  4885.3 1814.14  4984.8 1813.97  5053.2 1813.58  5053.5 1813.08
  5057.5 1813.08  5057.9 1813.58  5127.5 1814.25  5155.8 1814.26  5175.9 1814.61
    5206 1815.67  5253.3  1816.3  5306.3 1816.25  5376.5 1816.67  5406.6    1817
  5416.6  1817.3  5446.7 1817.72  5476.8 1817.74  5486.8 1817.58    5515 1818.19
    5520 1818.14  5526.9 1818.43    5547 1820.27    5557 1820.59  5601.4 1820.92
#Mann= 3 ,-1 , 0
  4609.6     .05       0  5053.2    .035       0  5057.9     .05       0
Bank Sta=5053.2,5057.9
XS Rating Curve= 0 ,0
Exp/Cntr=0.3,0.1

Type RM Length L Ch R = 1 ,28519   ,156,156,156
BEGIN DESCRIPTION:
Mapping XS b24aa69d
END DESCRIPTION:
XS GIS Cut Line= 4
      1592812.67      6813493.55      1593008.89      6813594.26
       1593644.3      6813710.58      1594118.27      6813710.58
#Sta/Elev= 30
  4490.1 1816.13  4532.4 1815.66    4538 1814.85  4582.6 1814.18  4928.2  1813.3
  4928.6  1812.8  4932.7  1812.8    4933  1813.3  5225.2  1814.1  5235.3 1814.33
  5254.8 1816.08  5265.8 1816.28  5437.3 1817.35  5467.3 1817.07  5517.3 1817.81
  5527.3 1817.36  5537.3 1816.22  5547.3 1817.64  5557.3 1818.07  5607.3 1818.34
  5617.3 1818.78  5627.3 1817.18  5647.3 1818.94  5657.3 1819.25  5667.3  1819.4
  5677.3 1818.74  5687.3 1819.51  5757.3 1820.92  5777.3    1822  5830.6 1822.88
#Mann= 3 ,-1 , 0
  4490.1     .05       0  4928.2    .035       0    4933     .05       0
Bank Sta=4928.2,4933
XS Rating Curve= 0 ,0
Exp/Cntr=0.3,0.1

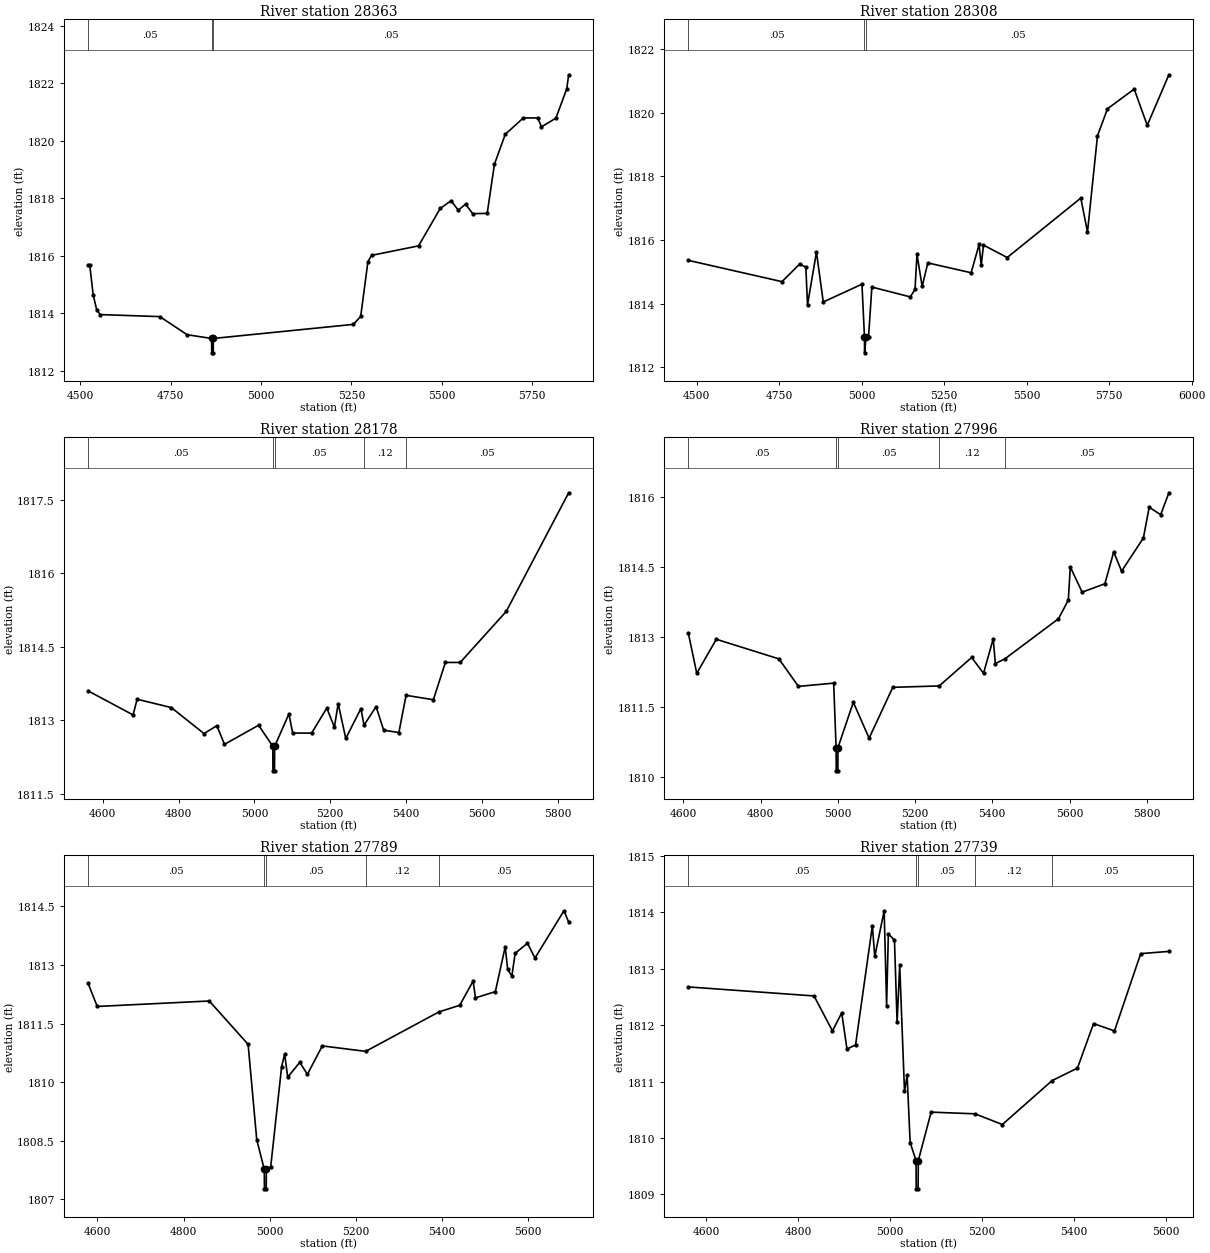
Type RM Length L Ch R = 1 ,28363   ,55,55,55
BEGIN DESCRIPTION:
Mapping XS efe990ac
END DESCRIPTION:
XS GIS Cut Line= 4
      1592771.06      6813797.39      1593083.54      6813790.44
      1593482.85      6813785.24      1594100.44      6813786.97
#Sta/Elev= 30
  4521.4 1815.67  4525.9 1815.67  4535.3 1814.64  4545.4  1814.1  4555.4 1813.95
  4719.7 1813.88  4795.4 1813.25    4863 1813.12  4863.4 1812.62  4867.5 1812.62
  4867.8 1813.12  5255.5 1813.61  5275.5 1813.89  5295.5 1815.79  5305.5 1816.01
  5435.5 1816.34  5495.5 1817.64  5525.5 1817.91  5545.5 1817.58  5565.5 1817.79
  5585.5 1817.46  5625.5 1817.47  5645.5 1819.18  5675.5 1820.22  5725.5 1820.79
  5765.5 1820.79  5775.5 1820.48  5815.5 1820.78  5845.5  1821.8  5850.9 1822.29
#Mann= 3 ,-1 , 0
  4521.4     .05       0    4863    .035       0  4867.8     .05       0
Bank Sta=4863,4867.8
XS Rating Curve= 0 ,0
Exp/Cntr=0.3,0.1

Type RM Length L Ch R = 1 ,28308   ,130,130,130
BEGIN DESCRIPTION:
Mapping XS 64981419
END DESCRIPTION:
XS GIS Cut Line= 6
       1592774.4      6813848.45      1592791.87      6813918.92
      1593286.67      6813830.38      1593354.37      6813901.56
      1593521.04       6813908.5      1594099.19      6813804.33
#Sta/Elev= 30
  4474.8 1815.36  4758.5 1814.69  4811.9 1815.24  4830.8 1815.15  4835.9 1813.96
    4863 1815.62  4883.6 1814.05  5000.9 1814.61  5008.5 1812.95  5008.8 1812.45
  5013.3 1812.95  5020.9 1812.96  5030.9 1814.52  5147.5 1814.21  5161.7 1814.45
  5167.6 1815.55  5183.3 1814.54  5200.5 1815.28  5331.8 1814.97  5355.8 1815.86
  5362.3  1815.2  5369.1 1815.84  5441.1 1815.45  5664.1 1817.32  5684.3 1816.25
  5714.6 1819.28  5744.9 1820.13  5825.8 1820.75  5865.4 1819.61    5931  1821.2
#Mann= 3 ,-1 , 0
  4474.8     .05       0  5008.5    .035       0  5013.3     .05       0
Bank Sta=5008.5,5013.3
XS Rating Curve= 0 ,0
Exp/Cntr=0.3,0.1

Type RM Length L Ch R = 1 ,28178   ,182,182,182
BEGIN DESCRIPTION:
Mapping XS db5032a1
END DESCRIPTION:
XS GIS Cut Line= 4
      1592765.87      6813979.68      1593116.53      6813960.58
       1593576.6       6813951.9      1594028.01      6813884.19
#Sta/Elev= 30
  4561.2  1813.6  4679.8 1813.11  4690.5 1813.43  4780.7 1813.26  4866.9 1812.73
  4900.8 1812.89  4920.9 1812.51  5010.9  1812.9  5048.4 1812.47  5048.8 1811.97
  5052.9 1811.97  5053.3 1812.47  5090.9 1813.13  5100.9 1812.74  5150.9 1812.74
  5190.9 1813.25  5210.9 1812.86  5220.9 1813.34  5240.9 1812.63  5280.9 1813.24
    5289  1812.9  5320.9 1813.28  5340.9  1812.8    5381 1812.75    5400 1813.51
    5472 1813.42  5503.7 1814.18  5542.8 1814.18  5664.2 1815.22    5829 1817.64
#Mann= 5 ,-1 , 0
  4561.2     .05       0  5048.4     .05       0  5053.3     .05       0
    5289     .12       0    5400     .05       0
Bank Sta=5048.4,5053.3
XS Rating Curve= 0 ,0
Exp/Cntr=0.3,0.1

Type RM Length L Ch R = 1 ,27996   ,207,207,207
BEGIN DESCRIPTION:
Elm 02 05 27995.72
END DESCRIPTION:
XS GIS Cut Line= 3
       1592773.5      6814187.57      1593157.25      6814125.27
      1593994.93      6813949.49
#Sta/Elev= 30
  4612.7 1813.08  4634.5 1812.22  4685.1 1812.95  4847.2 1812.53  4897.9 1811.94
  4989.1 1812.01  4995.4 1810.63  4995.8 1810.13  4999.9 1810.13  5000.3 1810.63
    5040  1811.6  5080.9 1810.83  5142.2 1811.92  5262.4 1811.95  5346.6 1812.56
  5377.2 1812.22  5402.4 1812.96  5407.9 1812.43  5432.5 1812.53  5571.4 1813.39
  5596.9 1813.79    5602  1814.5  5632.7 1813.96  5691.6 1814.14  5714.4 1814.82
  5734.9 1814.41  5791.3 1815.12  5806.4 1815.78  5836.1 1815.62  5857.4 1816.09
#Mann= 5 ,-1 , 0
  4612.7     .05       0  4995.4     .05       0  5000.3     .05       0
  5262.4     .12       0  5432.5     .05       0
Bank Sta=4995.4,5000.3
XS Rating Curve= 0 ,0
Exp/Cntr=0.3,0.1

Type RM Length L Ch R = 1 ,27789   ,50,50,50
BEGIN DESCRIPTION:
Elm 02 05 27788.7
END DESCRIPTION:
XS GIS Cut Line= 4
       1592783.9      6814329.93      1593204.12      6814317.55
      1593245.79      6814277.18      1593824.96      6814012.27
#Sta/Elev= 30
  4578.3 1812.53  4599.4 1811.94  4859.5 1812.08  4949.6 1810.97  4969.6 1808.53
  4987.1 1807.77  4987.5 1807.27  4991.6 1807.27    4992 1807.77    5002 1807.83
  5027.4  1810.4  5034.4 1810.72  5041.5 1810.13  5069.6 1810.51  5087.1  1810.2
  5121.8 1810.93  5222.4 1810.79  5392.4  1811.8  5440.7 1811.97  5471.8 1812.59
  5477.3 1812.16  5523.4 1812.32  5546.4 1813.47  5551.9 1812.89  5561.7 1812.72
  5569.4  1813.3  5597.9 1813.56  5615.4 1813.18  5682.6 1814.39  5693.6  1814.1
#Mann= 5 ,-1 , 0
  4578.3     .05       0  4987.1     .05       0    4992     .05       0
  5222.4     .12       0  5392.4     .05       0
Bank Sta=4987.1,4992
XS Rating Curve= 0 ,0
Exp/Cntr=0.3,0.1

Type RM Length L Ch R = 1 ,27739   ,52,52,52
BEGIN DESCRIPTION:
Elm 02 05 27738.6
END DESCRIPTION:
XS GIS Cut Line= 4
      1592792.63      6814409.79      1593170.27      6814380.05
      1593226.26      6814360.51      1593758.83      6814070.14
#Sta/Elev= 30
  4561.3 1812.68  4834.5 1812.52  4874.6  1811.9  4894.7 1812.22  4906.1 1811.58
  4924.8 1811.65  4961.3 1813.76  4966.6 1813.22    4987 1814.03  4992.3 1812.35
  4996.1 1813.62  5009.4 1813.51  5015.1 1812.05  5020.8 1813.06  5031.2 1810.83
  5036.9 1811.11  5043.5 1809.92  5056.3  1809.6  5056.7  1809.1  5060.8  1809.1
  5061.2  1809.6  5089.1 1810.46  5184.7 1810.43  5243.9 1810.24  5352.2 1811.02
  5407.2 1811.24  5442.2 1812.03  5487.7  1811.9  5544.7 1813.27    5606 1813.31
#Mann= 5 ,-1 , 0
  4561.3     .05       0  5056.3     .03       0  5061.2     .05       0
  5184.7     .12       0  5352.2     .05       0
Bank Sta=5056.3,5061.2
XS Rating Curve= 0 ,0
Exp/Cntr=0.3,0.1

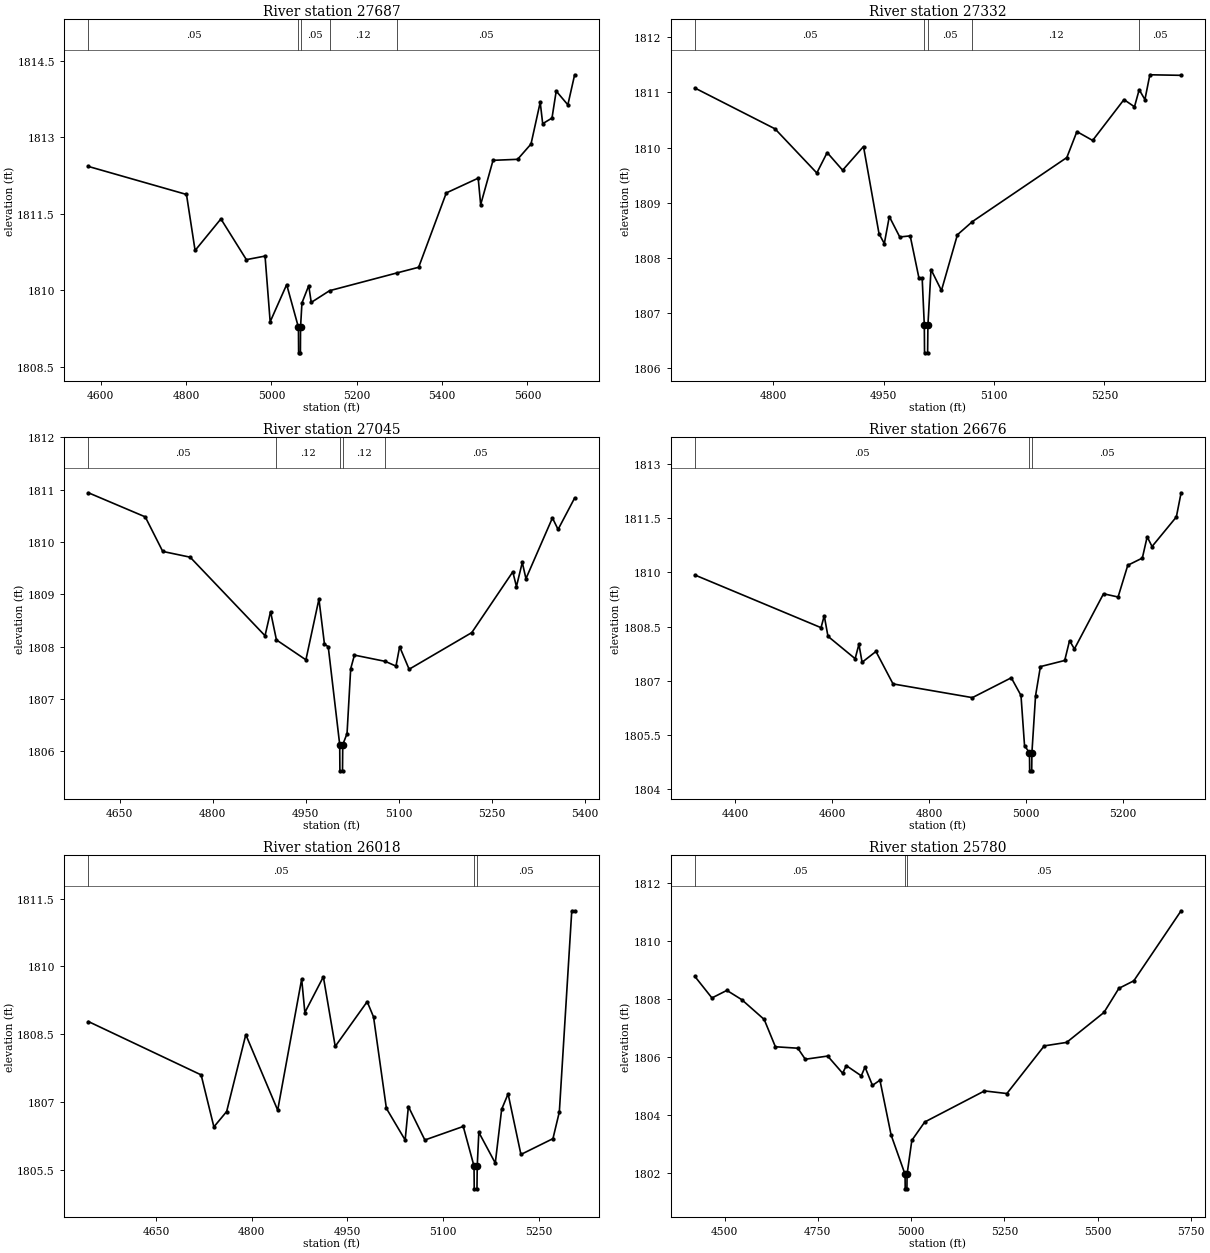
Type RM Length L Ch R = 1 ,27687   ,355,355,355
BEGIN DESCRIPTION:
Elm 02 05 27686.77
END DESCRIPTION:
XS GIS Cut Line= 4
      1592847.34      6814480.97      1593197.61      6814432.13
      1593262.72      6814396.97      1593881.12       6814043.6
#Sta/Elev= 30
  4570.8 1812.43  4800.7 1811.88  4820.9 1810.78  4881.4  1811.4  4941.1  1810.6
  4984.9 1810.67  4996.9 1809.38  5035.6 1810.11  5063.2 1809.27  5063.6 1808.77
  5067.8 1808.77  5068.1 1809.27  5071.4 1809.75  5087.3 1810.09  5093.2 1809.76
  5136.1 1809.99  5294.5 1810.34    5345 1810.45  5409.8 1811.91  5484.6  1812.2
  5490.4 1811.68  5519.4 1812.55    5577 1812.57  5608.4 1812.87    5630 1813.69
  5635.8 1813.27  5657.6 1813.38  5667.5 1813.91  5694.8 1813.64  5710.7 1814.23
#Mann= 5 ,-1 , 0
  4570.8     .05       0  5063.2     .03       0  5068.1     .05       0
  5136.1     .12       0  5294.5     .05       0
Bank Sta=5063.2,5068.1
XS Rating Curve= 0 ,0
Exp/Cntr=0.3,0.1

Type RM Length L Ch R = 1 ,27332   ,287,287,287
BEGIN DESCRIPTION:
Elm 02 05 27332.29
END DESCRIPTION:
XS GIS Cut Line= 3
      1593330.17      6814697.13      1593556.77      6814490.07
      1593820.53       6814253.6
#Sta/Elev= 30
  4693.1 1811.08  4802.1 1810.34  4858.9 1809.54    4873 1809.91    4894 1809.59
  4922.4 1810.02  4943.5 1808.44  4950.7 1808.26  4957.5 1808.75  4971.7 1808.38
  4985.9  1808.4  4997.9 1807.63  5002.2 1807.63  5005.1 1806.78  5005.4 1806.28
  5009.6 1806.28    5010 1806.78  5014.2 1807.79  5028.4 1807.41  5050.1 1808.42
  5070.6 1808.66  5198.9 1809.82  5212.6 1810.29    5234 1810.13  5276.6 1810.87
  5290.9 1810.74  5297.3 1811.05  5305.1 1810.87  5311.8 1811.32  5354.3 1811.31
#Mann= 5 ,-1 , 0
  4693.1     .05       0  5005.1     .05       0    5010     .05       0
  5070.6     .12       0  5297.3     .05       0
Bank Sta=5005.1,5010
XS Rating Curve= 0 ,0
Exp/Cntr=0.3,0.1

Type RM Length L Ch R = 1 ,27045   ,369,369,369
BEGIN DESCRIPTION:
Elm 02 05 27044.82
END DESCRIPTION:
XS GIS Cut Line= 3
      1593554.17      6814993.97      1593778.12      6814661.95
      1593982.56      6814337.71
#Sta/Elev= 30
  4599.5 1810.94  4691.1 1810.48  4719.3 1809.82  4763.5 1809.71  4884.2 1808.21
  4893.1 1808.67  4902.6 1808.13  4950.1 1807.75  4971.1 1808.91    4980 1808.05
  4986.1    1808  5004.6 1806.13  5004.9 1805.63  5009.1 1805.63  5009.5 1806.13
  5016.4 1806.34  5022.3 1807.58  5028.3 1807.84  5078.2 1807.72  5095.3 1807.63
  5101.2    1808  5116.5 1807.57  5217.5 1808.27  5283.6 1809.43  5289.5 1809.15
  5298.9 1809.61  5304.8  1809.3  5347.5 1810.46  5356.6 1810.24  5383.3 1810.84
#Mann= 5 ,-1 , 0
  4599.5     .05       0  4902.6     .12       0  5004.6     .07       0
  5009.5     .12       0  5078.2     .05       0
Bank Sta=5004.6,5009.5
XS Rating Curve= 0 ,0
Exp/Cntr=0.3,0.1

Type RM Length L Ch R = 1 ,26676   ,658,658,658
BEGIN DESCRIPTION:
Elm 02 05 26675.73
END DESCRIPTION:
XS GIS Cut Line= 4
       1593662.4      6815121.47      1594087.82      6814764.58
      1594095.83      6814638.51      1594104.95      6814318.16
#Sta/Elev= 30
  4317.6 1809.93  4577.6 1808.47  4584.2  1808.8  4591.9 1808.23  4647.9 1807.61
  4655.7 1808.01  4662.2 1807.51  4690.8 1807.81    4726 1806.91  4889.5 1806.53
  4969.7 1807.08  4989.7 1806.59    4997  1805.2  5007.2    1805  5007.6  1804.5
  5011.8  1804.5  5012.2    1805  5019.7 1806.58  5029.7 1807.39  5079.8 1807.56
  5089.8 1808.11  5099.8 1807.88  5159.8 1809.41  5189.8 1809.32  5209.8  1810.2
  5239.8  1810.4  5249.8 1810.99  5259.8 1810.72  5309.9 1811.54  5319.7 1812.21
#Mann= 3 ,-1 , 0
  4317.6     .05       0  5007.2     .05       0  5012.2     .05       0
Bank Sta=5007.2,5012.2
XS Rating Curve= 0 ,0
Exp/Cntr=0.3,0.1

Type RM Length L Ch R = 1 ,26018   ,238,238,238
BEGIN DESCRIPTION:
Elm 02 05 26017.75
END DESCRIPTION:
XS GIS Cut Line= 4
      1593848.47      6815180.18      1594213.02      6815194.06
       1594303.3      6815187.12      1594608.88      6815159.34
#Sta/Elev= 30
  4544.1 1808.78  4720.8  1807.6  4740.8 1806.45  4760.8 1806.79  4790.8 1808.49
  4840.8 1806.82  4878.4 1809.72  4883.4 1808.98  4912.4 1809.77    4931 1808.23
  4981.1 1809.22  4991.1 1808.88  5011.2 1806.86  5040.6 1806.16  5045.7  1806.9
  5071.5 1806.16  5131.7 1806.46  5148.6 1805.58  5148.9 1805.08  5153.2 1805.08
  5153.6 1805.58  5156.1 1806.33  5181.9 1805.65  5191.9 1806.84    5202 1807.18
  5222.1 1805.84  5272.3 1806.19  5282.3 1806.78  5301.8 1811.23  5306.3 1811.23
#Mann= 3 ,-1 , 0
  4544.1     .05       0  5148.6     .05       0  5153.6     .05       0
Bank Sta=5148.6,5153.6
XS Rating Curve= 0 ,0
Exp/Cntr=0.3,0.1

Type RM Length L Ch R = 1 ,25780   ,277,277,277
BEGIN DESCRIPTION:
Elm 02 05 25779.85
END DESCRIPTION:
XS GIS Cut Line= 3
       1593829.3      6815397.19      1594410.94      6815385.04
      1595131.62      6815365.98
#Sta/Elev= 30
  4420.6 1808.77  4466.3 1808.03  4506.3 1808.29  4546.3 1807.97  4606.3 1807.29
  4636.3 1806.35  4696.4  1806.3  4716.4 1805.92  4776.4 1806.03  4816.4 1805.44
  4826.4  1805.7  4866.4 1805.35  4876.4 1805.65  4896.4 1805.02  4916.4  1805.2
  4946.4 1803.31  4983.7 1801.96  4984.1 1801.46  4988.7 1801.46  4989.1 1801.96
  5001.9 1803.13  5036.4 1803.76  5196.5 1804.83  5256.5 1804.74  5356.6 1806.38
  5416.6  1806.5  5516.6 1807.53  5556.6 1808.36  5596.6 1808.62  5723.3 1811.03
#Mann= 3 ,-1 , 0
  4420.6     .05       0  4983.7     .03       0  4989.1     .05       0
Bank Sta=4983.7,4989.1
XS Rating Curve= 0 ,0
Exp/Cntr=0.3,0.1

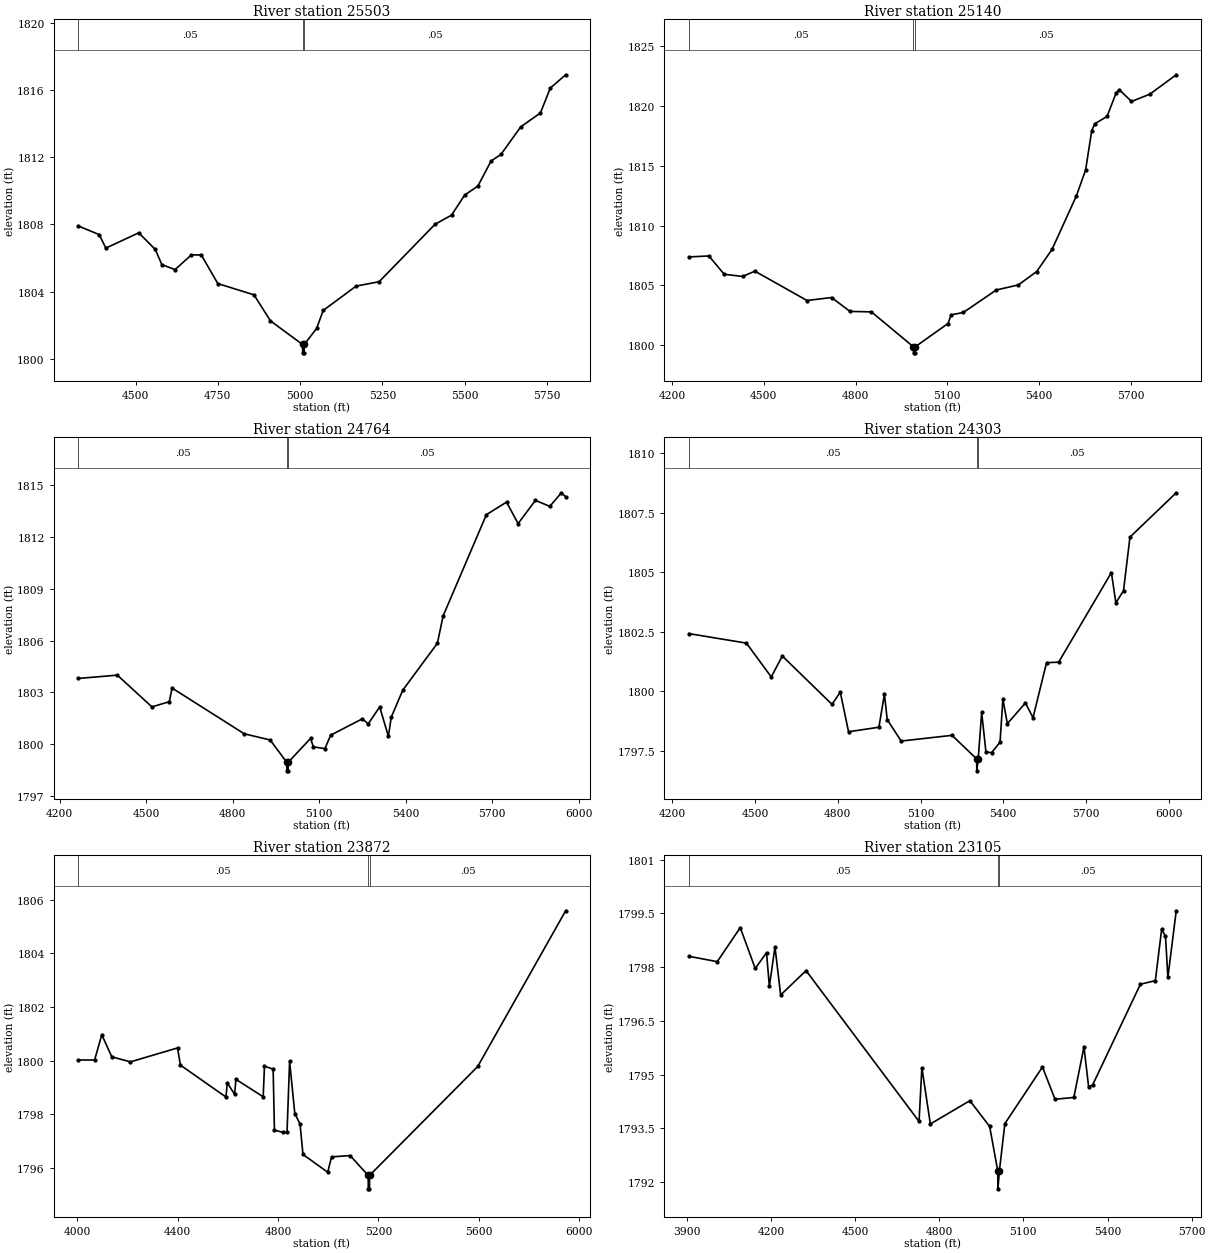
Type RM Length L Ch R = 1 ,25503   ,363,363,363
BEGIN DESCRIPTION:
Elm 02 05 25502.95
END DESCRIPTION:
XS GIS Cut Line= 3
       1593831.1       6815646.9      1594505.99      6815631.71
      1595311.63      6815629.54
#Sta/Elev= 30
  4325.9 1807.91  4389.8 1807.39  4409.8 1806.59  4509.8  1807.5  4559.9 1806.51
  4579.9 1805.61  4619.9 1805.31  4669.9 1806.19  4699.9 1806.18  4749.9 1804.48
  4859.9 1803.81  4909.9 1802.26  5007.2 1800.86  5007.7 1800.36  5012.3 1800.36
  5012.7 1800.86    5050 1801.81    5070 1802.88    5170 1804.33    5240 1804.59
    5410 1808.01    5460 1808.55    5500 1809.75    5540 1810.28    5580 1811.77
    5610 1812.16    5670  1813.8    5730 1814.63    5760 1816.11  5806.6  1816.9
#Mann= 3 ,-1 , 0
  4325.9     .05       0  5007.2     .05       0  5012.7     .05       0
Bank Sta=5007.2,5012.7
XS Rating Curve= 0 ,0
Exp/Cntr=0.3,0.1

Type RM Length L Ch R = 1 ,25140   ,376,376,376
BEGIN DESCRIPTION:
Elm 02 05 25140.14
END DESCRIPTION:
XS GIS Cut Line= 3
       1593709.5       6815922.5      1594449.56      6815978.93
      1595301.25      6815991.93
#Sta/Elev= 30
  4254.6 1807.38  4320.3 1807.46  4370.4 1805.93  4430.6 1805.75  4470.7 1806.19
  4641.2 1803.74  4721.5 1803.99  4781.6 1802.83  4851.8 1802.79  4989.3 1799.87
  4989.7 1799.37  4994.3 1799.37  4994.8 1799.87  5102.3 1801.82  5112.3 1802.54
  5152.3 1802.74  5260.3 1804.62  5332.3 1805.04  5392.3 1806.16  5442.3    1808
  5522.3 1812.49  5552.3 1814.65  5572.3 1817.93  5582.3  1818.5  5622.3 1819.11
  5652.3 1821.09  5662.3 1821.35  5702.3 1820.36  5762.3 1820.97  5848.6 1822.59
#Mann= 3 ,-1 , 0
  4254.6     .05       0  4989.3    .035       0  4994.8     .05       0
Bank Sta=4989.3,4994.8
XS Rating Curve= 0 ,0
Exp/Cntr=0.3,0.1

Type RM Length L Ch R = 1 ,24764   ,461,461,461
BEGIN DESCRIPTION:
Elm 02 05 24763.88
END DESCRIPTION:
XS GIS Cut Line= 3
       1593669.3      6816346.26      1594407.17      6816339.75
      1595359.86      6816335.41
#Sta/Elev= 30
  4263.9  1803.8  4399.6 1803.99  4519.6 1802.15  4579.6 1802.45  4589.6 1803.24
  4839.6 1800.59  4929.6 1800.23  4986.9 1798.94  4987.3 1798.44  4991.9 1798.44
  4992.4 1798.94  5069.6 1800.32  5079.6 1799.83  5119.6 1799.73  5139.6 1800.51
  5249.6 1801.46  5269.6 1801.16  5309.6 1802.15  5339.6 1800.44  5349.6 1801.55
  5389.6 1803.12  5509.6 1805.84  5529.6 1807.43  5679.6  1813.3  5749.6 1814.03
  5789.6 1812.78  5849.6 1814.13  5899.6 1813.78  5939.6 1814.57  5954.5 1814.34
#Mann= 3 ,-1 , 0
  4263.9     .05       0  4986.9    .035       0  4992.4     .05       0
Bank Sta=4986.9,4992.4
XS Rating Curve= 0 ,0
Exp/Cntr=0.3,0.1

Type RM Length L Ch R = 1 ,24303   ,431,431,431
BEGIN DESCRIPTION:
Elm 02 05 24302.6
END DESCRIPTION:
XS GIS Cut Line= 3
      1593666.26      6816819.21      1594408.48      6816800.98
      1595408.81      6816582.73
#Sta/Elev= 30
  4260.4 1802.42  4469.2 1802.02  4559.2  1800.6  4599.2 1801.48  4779.3 1799.45
  4809.3 1799.96  4839.3  1798.3  4949.3 1798.49  4969.3 1799.88  4979.4 1798.81
    5030 1797.91  5214.2 1798.15  5303.5 1797.16    5304 1796.66  5309.1 1797.16
  5321.7 1799.11    5337 1797.46  5357.5 1797.42  5388.2 1797.86  5398.5 1799.67
  5414.7 1798.64  5480.3 1799.51  5507.7 1798.89  5556.7  1801.2  5600.6 1801.22
  5791.7 1804.98  5807.9 1803.71  5835.6 1804.22    5859 1806.47  6026.7 1808.33
#Mann= 3 ,-1 , 0
  4260.4     .05       0  5303.5    .035       0  5309.1     .05       0
Bank Sta=5303.5,5309.1
XS Rating Curve= 0 ,0
Exp/Cntr=0.3,0.1

Type RM Length L Ch R = 1 ,23872   ,767,767,767
BEGIN DESCRIPTION:
Elm 02 05 23871.85
END DESCRIPTION:
XS GIS Cut Line= 3
      1593622.06      6817428.57      1594582.96      6817165.56
      1595410.55      6816704.92
#Sta/Elev= 30
  4003.3 1800.03  4068.6 1800.03  4097.3 1800.97    4137 1800.15  4211.2 1799.96
  4399.2 1800.48  4410.7 1799.84  4592.4 1798.65  4597.5 1799.18  4626.9 1798.75
    4632 1799.31  4740.7 1798.66  4745.9  1799.8  4780.4 1799.69  4785.6 1797.42
    4820 1797.33  4835.8 1797.34  4846.1 1799.98  4866.9 1798.03  4887.6 1797.65
  4899.4 1796.51    4998 1795.85  5013.3 1796.42  5087.4 1796.47  5159.3 1795.73
  5159.8 1795.23  5164.5 1795.23  5164.9 1795.73  5596.2 1799.79  5946.7 1805.59
#Mann= 3 ,-1 , 0
  4003.3     .05       0  5159.3     .05       0  5164.9     .05       0
Bank Sta=5159.3,5164.9
XS Rating Curve= 0 ,0
Exp/Cntr=0.3,0.1

Type RM Length L Ch R = 1 ,23105   ,368,368,368
BEGIN DESCRIPTION:
Elm 02 05 23105.33
END DESCRIPTION:
XS GIS Cut Line= 3
       1593819.9       6817795.2      1594900.66      6817664.99
      1595481.61      6817374.51
#Sta/Elev= 30
    3907  1798.3  4008.4 1798.15  4090.5  1799.1  4143.8 1797.96  4184.1  1798.4
  4194.2 1797.46  4214.3 1798.56  4234.5 1797.22  4325.1  1797.9    4728 1793.69
  4738.1 1795.19  4768.3 1793.62  4909.3 1794.27  4979.8 1793.55  5008.7 1792.31
  5009.2 1791.81  5014.5 1792.31    5034 1793.63  5168.1 1795.21  5212.9 1794.31
  5279.9 1794.36  5316.1 1795.77  5332.8 1794.65    5347 1794.71  5517.3 1797.52
  5570.6 1797.62    5593 1799.05  5606.8 1798.86  5615.3 1797.71  5645.1 1799.57
#Mann= 3 ,-1 , 0
    3907     .05       0  5008.7     .05       0  5014.5     .05       0
Bank Sta=5008.7,5014.5
XS Rating Curve= 0 ,0
Exp/Cntr=0.3,0.1