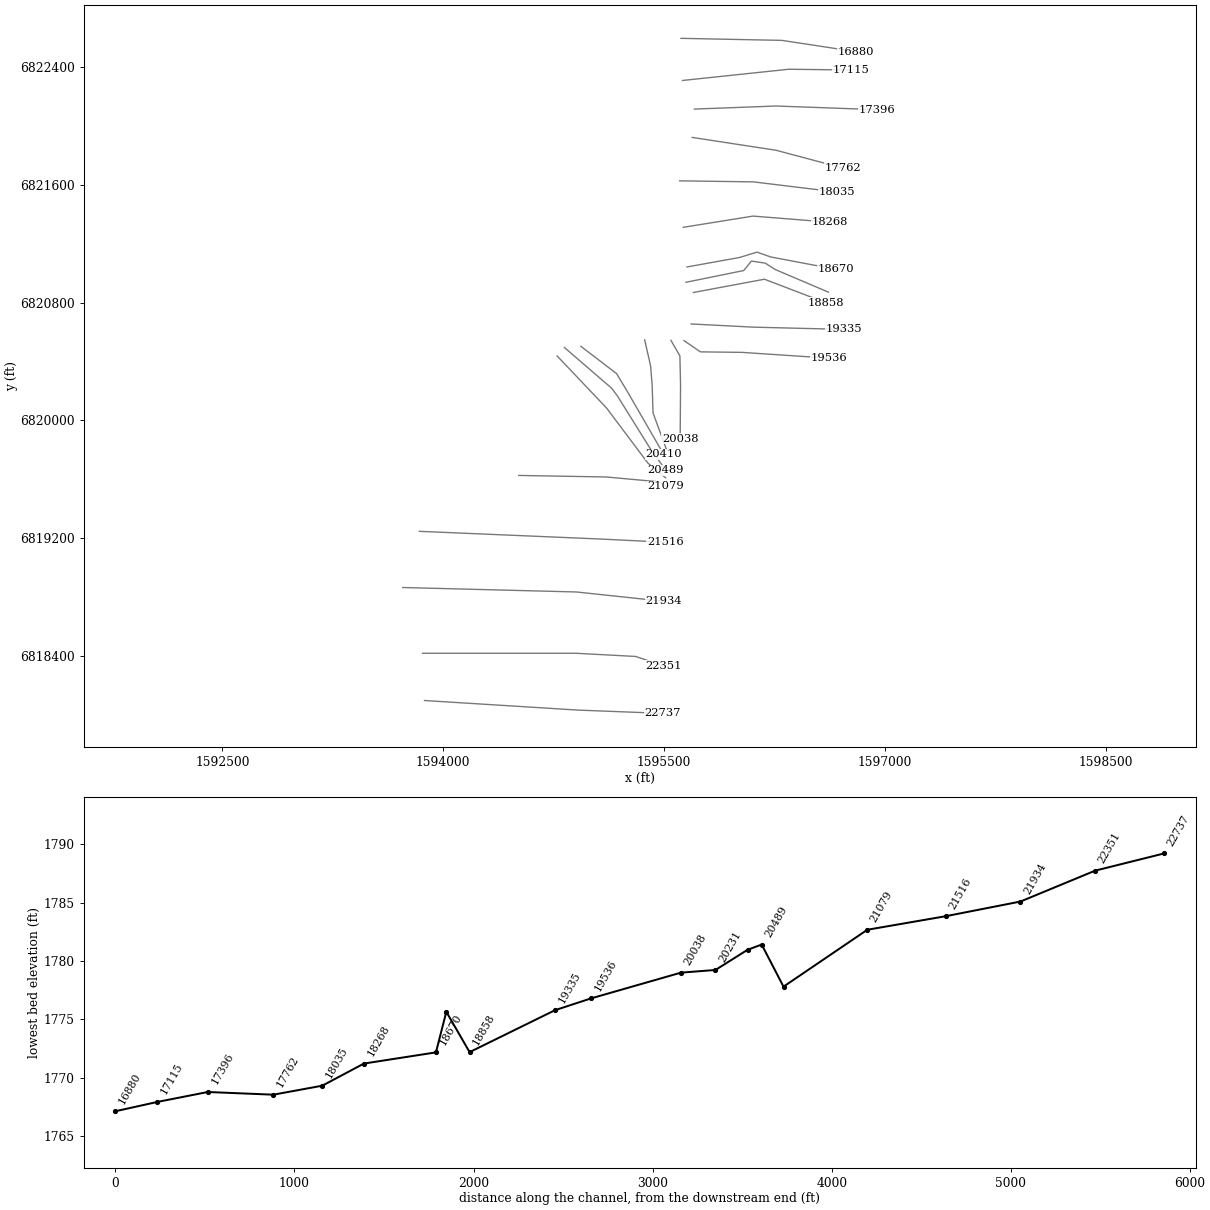
HEC-RAS study Elm 02 05.prj: Elm 02 05 Base Level Engineering

--- Elm 02 05.g01 (geometry) --- (continued)

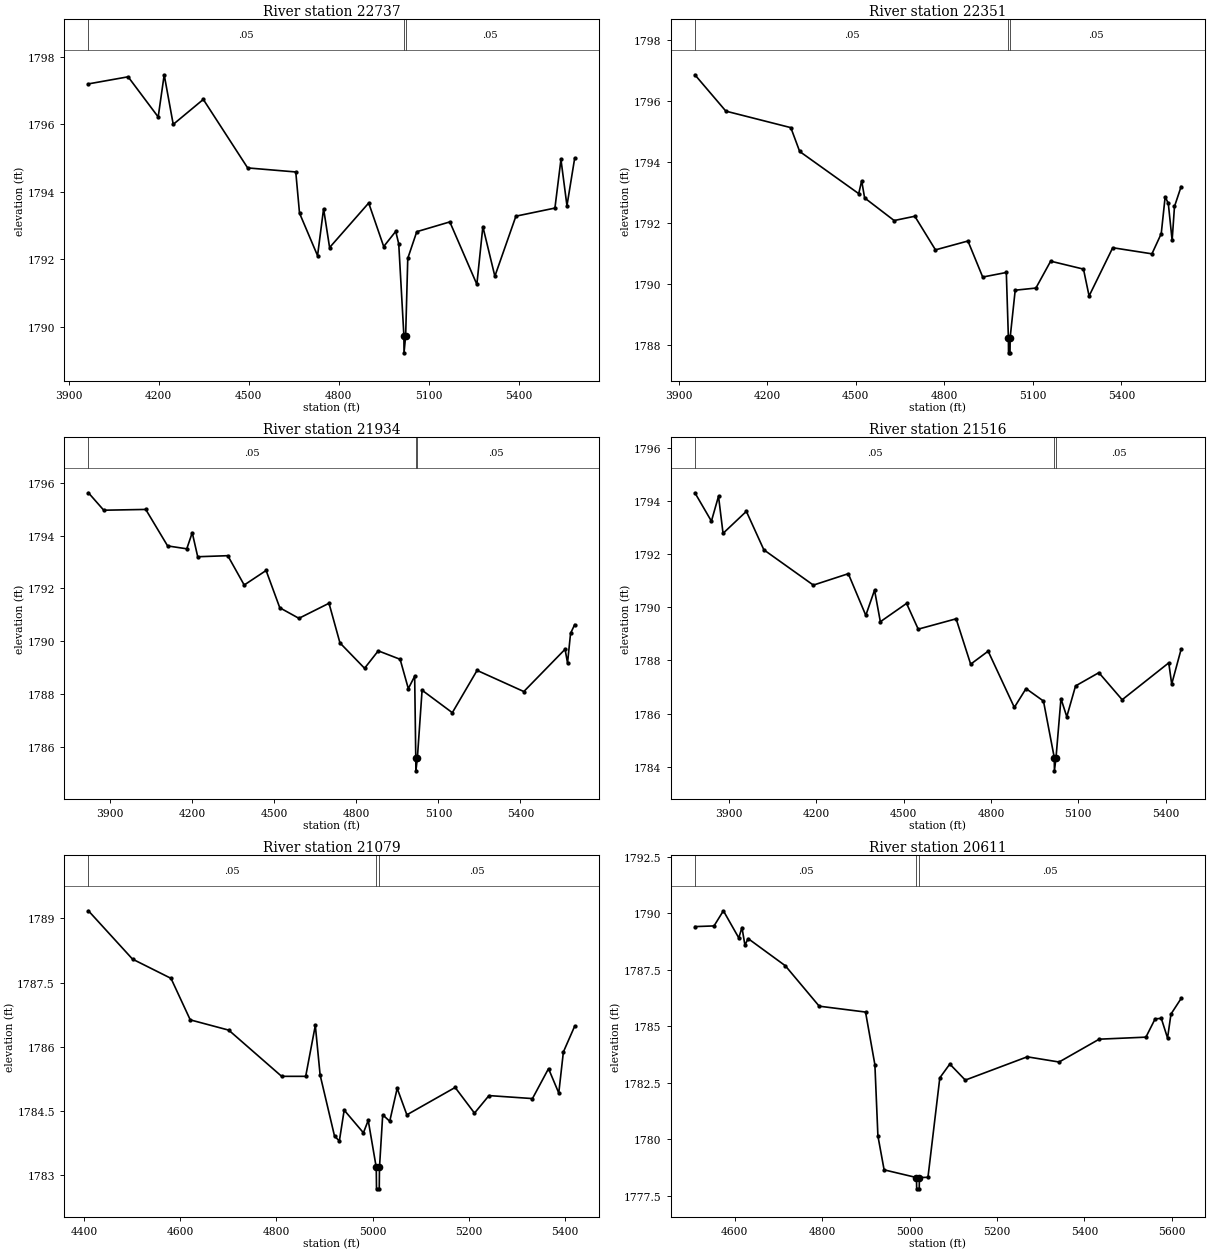
Type RM Length L Ch R = 1 ,22737   ,386,386,386
BEGIN DESCRIPTION:
Elm 02 05 22736.57
END DESCRIPTION:
XS GIS Cut Line= 3
      1593872.97      6818096.25      1594914.65      6818031.15
       1595490.6      6818008.81
#Sta/Elev= 30
  3966.2  1797.2  4098.5 1797.41  4198.7 1796.22  4218.7 1797.47  4248.8    1796
    4349 1796.74  4496.8 1794.71  4657.1 1794.59  4669.6 1793.37  4729.7 1792.11
  4749.8  1793.5  4769.8 1792.35  4900.1 1793.67  4950.1 1792.38  4990.2 1792.83
  5000.2 1792.46  5017.4 1789.73  5017.8 1789.23  5023.2 1789.73  5030.3 1792.03
  5060.3 1792.82  5170.4 1793.11  5260.5 1791.26  5280.5 1792.97  5320.5  1791.5
  5390.6 1793.28  5520.6 1793.52  5540.7 1794.96  5560.7 1793.59  5586.3 1794.99
#Mann= 3 ,-1 , 0
  3966.2     .05       0  5017.4     .05       0  5023.2     .05       0
Bank Sta=5017.4,5023.2
XS Rating Curve= 0 ,0
Exp/Cntr=0.3,0.1

Type RM Length L Ch R = 1 ,22351   ,417,417,417
BEGIN DESCRIPTION:
Elm 02 05 22351.38
END DESCRIPTION:
XS GIS Cut Line= 4
        1593860.      6818417.43      1594901.63      6818417.43
      1595307.12      6818395.79      1595496.19      6818332.43
#Sta/Elev= 30
  3955.1 1796.85  4060.1 1795.66  4280.1 1795.12  4310.1 1794.34  4510.1 1792.96
  4520.1 1793.38  4530.1 1792.82  4630.1 1792.08  4700.1 1792.22  4770.1 1791.12
  4880.1 1791.41  4930.1 1790.23  5010.1 1790.38  5017.1 1788.25  5017.6 1787.75
  5022.6 1787.75  5023.1 1788.25  5040.2  1789.8  5110.3 1789.87  5160.3 1790.75
  5271.5 1790.49  5290.5 1789.61  5370.6 1791.19  5503.4 1790.99  5534.9 1791.65
  5548.2 1792.86  5558.8 1792.64  5571.8 1791.43  5579.8 1792.54  5602.2 1793.19
#Mann= 3 ,-1 , 0
  3955.1     .05       0  5017.1     .05       0  5023.1     .05       0
Bank Sta=5017.1,5023.1
XS Rating Curve= 0 ,0
Exp/Cntr=0.3,0.1

Type RM Length L Ch R = 1 ,21934   ,418,418,418
BEGIN DESCRIPTION:
Elm 02 05 21934.22
END DESCRIPTION:
XS GIS Cut Line= 3
      1593725.45      6818864.48      1594905.97       6818834.1
      1595499.78      6818770.66
#Sta/Elev= 30
    3820 1795.62  3876.1 1794.96  4029.6 1794.99  4109.6 1793.61  4179.7  1793.5
  4199.7 1794.11  4219.7  1793.2  4329.7 1793.24  4389.7 1792.13  4469.8 1792.68
  4519.8 1791.27  4589.8 1790.87  4699.8 1791.44  4739.9 1789.94  4829.9 1788.98
  4879.9 1789.64  4959.9 1789.32  4989.9 1788.21  5013.1 1788.68  5017.1  1785.6
  5017.6  1785.1  5023.1  1785.6  5040.2 1788.15  5150.8  1787.3  5241.3  1788.9
  5412.3  1788.1  5563.1  1789.7  5572.1 1789.18  5583.2  1790.3  5598.1 1790.63
#Mann= 3 ,-1 , 0
    3820     .05       0  5017.1     .05       0  5023.1     .05       0
Bank Sta=5017.1,5023.1
XS Rating Curve= 0 ,0
Exp/Cntr=0.3,0.1

Type RM Length L Ch R = 1 ,21516   ,437,437,437
BEGIN DESCRIPTION:
Elm 02 05 21516.17
END DESCRIPTION:
XS GIS Cut Line= 3
      1593838.25      6819246.43      1595062.22      6819194.34
       1595507.3      6819172.53
#Sta/Elev= 30
  3782.4 1794.32  3839.2 1793.25  3863.6 1794.19  3879.2 1792.79  3959.3 1793.62
  4019.4 1792.17  4189.5 1790.84  4309.6 1791.27  4369.7  1789.7  4399.7 1790.65
  4419.7 1789.46  4509.8 1790.15  4549.8 1789.18    4680 1789.57    4730 1787.86
  4790.1 1788.35  4880.1 1786.23  4920.2 1786.94  4980.2 1786.47  5017.3 1784.34
  5017.8 1783.84  5023.3 1784.34  5040.3 1786.56  5060.3 1785.88  5090.4 1787.04
  5170.5 1787.54  5250.6 1786.52  5410.7 1787.91  5420.8 1787.11  5453.1 1788.42
#Mann= 3 ,-1 , 0
  3782.4     .05       0  5017.3     .05       0  5023.3     .05       0
Bank Sta=5017.3,5023.3
XS Rating Curve= 0 ,0
Exp/Cntr=0.3,0.1

Type RM Length L Ch R = 1 ,21079   ,468,468,468
BEGIN DESCRIPTION:
Elm 02 05 21079.18
END DESCRIPTION:
XS GIS Cut Line= 4
      1594513.36      6819626.34      1595107.07      6819615.93
      1595465.56      6819583.09      1595514.18      6819553.32
#Sta/Elev= 30
  4409.3 1789.18    4501 1788.05    4581  1787.6    4621 1786.63    4701 1786.39
    4811 1785.31    4861 1785.31    4881  1786.5    4891 1785.34    4921 1783.91
    4931  1783.8    4941 1784.52    4981 1783.99    4991 1784.28  5007.7 1783.18
  5008.2 1782.68  5013.9 1782.68  5014.4 1783.18  5021.1 1784.41  5035.7 1784.26
  5051.2 1785.03  5071.3 1784.41  5171.7 1785.05  5211.9 1784.45    5242 1784.86
  5332.4 1784.79  5365.8 1785.49  5387.1 1784.92  5396.7 1785.88  5420.1 1786.48
#Mann= 3 ,-1 , 0
  4409.3     .05       0  5007.7     .05       0  5014.4     .05       0
Bank Sta=5007.7,5014.4
XS Rating Curve= 0 ,0
Exp/Cntr=0.3,0.1

Type RM Length L Ch R = 1 ,20611   ,122,122,122
BEGIN DESCRIPTION:
Elm 02 05 20611.31
END DESCRIPTION:
XS GIS Cut Line= 4
      1594773.75      6820438.83      1595109.68      6820084.68
      1595390.33      6819710.47      1595510.72       6819610.6
#Sta/Elev= 30
  4508.7  1789.4  4552.5 1789.43  4573.9  1790.1  4609.1  1788.9  4616.4 1789.36
  4623.2 1788.58  4630.5 1788.87  4715.5 1787.67  4793.1 1785.88  4899.1 1785.62
  4920.5 1783.29  4927.4 1780.14  4941.6 1778.64  5015.6  1778.3  5016.1  1777.8
  5021.9  1777.8  5022.4  1778.3  5041.9 1778.31    5069 1782.71  5091.9 1783.32
  5127.3 1782.61    5269 1783.64  5341.9 1783.41  5433.6 1784.42  5540.5 1784.51
  5561.6 1785.32  5575.7 1785.34    5590 1784.47  5597.8 1785.53    5621 1786.22
#Mann= 3 ,-1 , 0
  4508.7     .05       0  5015.6     .05       0  5022.4     .05       0
Bank Sta=5015.6,5022.4
XS Rating Curve= 0 ,0
Exp/Cntr=0.3,0.1

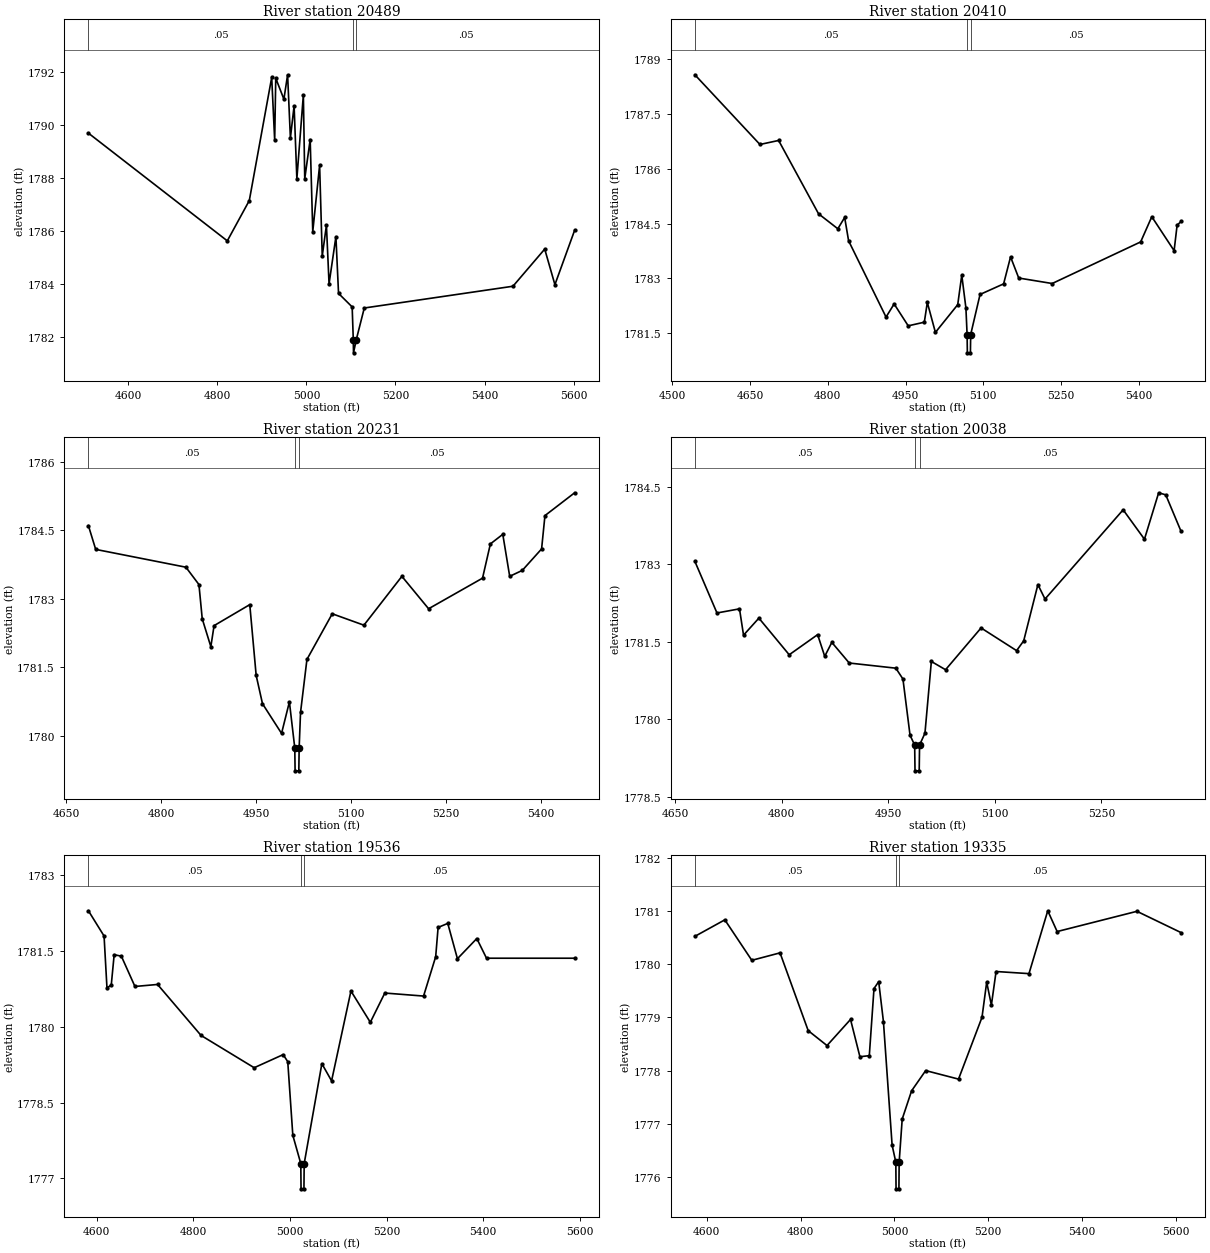
Type RM Length L Ch R = 1 ,20489   ,79,79,79
BEGIN DESCRIPTION:
Elm 02 05 20488.84
END DESCRIPTION:
XS GIS Cut Line= 5
      1594823.18      6820496.17      1595143.53       6820220.1
      1595182.59      6820168.01      1595405.17      6819810.96
       1595511.7      6819661.97
#Sta/Elev= 30
  4510.5 1789.69  4822.4 1785.63  4871.8 1787.15  4922.1 1791.79  4928.8 1789.42
  4931.2 1791.76  4949.5 1790.97  4957.8 1791.89  4964.1 1789.51  4972.4 1790.72
  4978.6 1787.97  4993.2 1791.13  4996.3 1787.97  5008.5 1789.45  5014.3 1785.98
  5029.7 1788.48  5035.6 1785.06    5045 1786.22  5050.9 1784.01  5066.3 1785.79
  5072.2 1783.65  5102.8 1783.14  5105.3 1781.91  5105.8 1781.41  5112.1 1781.91
    5130  1783.1  5463.9 1783.92  5535.2 1785.32  5558.1 1783.98  5602.4 1786.03
#Mann= 3 ,-1 , 0
  4510.5     .05       0  5105.3     .05       0  5112.1     .05       0
Bank Sta=5105.3,5112.1
XS Rating Curve= 0 ,0
Exp/Cntr=0.3,0.1

Type RM Length L Ch R = 1 ,20410   ,179,179,179
BEGIN DESCRIPTION:
Elm 02 05 20410.28
END DESCRIPTION:
XS GIS Cut Line= 4
      1594935.17      6820503.97      1595177.39      6820319.05
      1595255.51      6820188.85      1595496.71      6819771.28
#Sta/Elev= 30
  4543.3 1788.58  4668.9 1786.67    4705 1786.78  4782.1 1784.77  4819.3 1784.36
  4832.5 1784.67  4840.1 1784.03  4912.4 1781.94    4928  1782.3  4955.2  1781.7
  4986.3  1781.8  4992.1 1782.34  5007.7 1781.52  5050.8 1782.28  5058.6 1783.09
  5066.6 1782.19  5068.9 1781.46  5069.4 1780.96  5075.3 1780.96  5075.8 1781.46
  5093.9 1782.56  5139.4 1782.85  5152.8 1783.59  5168.6 1783.01  5233.2 1782.86
    5404    1784  5425.5 1784.69  5468.6 1783.76  5474.4 1784.46  5482.1 1784.56
#Mann= 3 ,-1 , 0
  4543.3     .05       0  5068.9     .05       0  5075.8     .05       0
Bank Sta=5068.9,5075.8
XS Rating Curve= 0 ,0
Exp/Cntr=0.3,0.1

Type RM Length L Ch R = 1 ,20231   ,193,193,193
BEGIN DESCRIPTION:
Elm 02 05 20230.68
END DESCRIPTION:
XS GIS Cut Line= 5
      1595368.32      6820548.12      1595408.59      6820372.81
      1595419.57      6820238.32      1595425.29      6820051.59
      1595517.05      6819801.42
#Sta/Elev= 30
  4685.3  1784.6  4696.8 1784.08  4839.3 1783.69  4859.9 1783.31  4865.1 1782.56
  4878.7 1781.95  4883.8 1782.41  4940.2 1782.87  4950.3 1781.32  4960.3  1780.7
  4990.4 1780.05  5002.8 1780.74  5011.3 1779.73  5011.8 1779.23  5017.7 1779.23
  5018.2 1779.73  5020.4 1780.51  5030.5 1781.67  5070.5 1782.67  5120.5 1782.42
  5180.5 1783.49  5222.7 1782.78  5307.9 1783.45  5320.3  1784.2  5339.9 1784.41
  5350.8 1783.49  5370.7 1783.62  5401.2 1784.09  5406.5 1784.82  5453.4 1785.32
#Mann= 3 ,-1 , 0
  4685.3     .05       0  5011.3     .03       0  5018.2     .05       0
Bank Sta=5011.3,5018.2
XS Rating Curve= 0 ,0
Exp/Cntr=0.3,0.1

Type RM Length L Ch R = 1 ,20038   ,502,502,502
BEGIN DESCRIPTION:
Elm 02 05 20037.98
END DESCRIPTION:
XS GIS Cut Line= 4
      1595547.15      6820544.64       1595607.9      6820438.76
      1595612.28      6820240.93      1595609.68      6819876.39
#Sta/Elev= 30
  4677.6 1783.06  4708.7 1782.06  4740.4 1782.14  4746.1 1781.63  4767.7 1781.96
  4810.4 1781.25  4850.4 1781.64  4860.4 1781.22  4870.4 1781.49  4894.9 1781.09
  4960.5 1780.99  4970.5 1780.78  4980.5 1779.69    4987  1779.5  4987.5    1779
  4993.4    1779  4993.9  1779.5  5001.5 1779.73  5010.5 1781.12  5030.5 1780.96
  5080.5 1781.77  5130.5 1781.33  5140.5 1781.52  5160.5 1782.61  5170.5 1782.33
  5280.5 1784.06  5310.5 1783.49  5330.5 1784.39  5340.5 1784.35  5362.1 1783.64
#Mann= 3 ,-1 , 0
  4677.6     .05       0    4987     .03       0  4993.9     .05       0
Bank Sta=4987,4993.9
XS Rating Curve= 0 ,0
Exp/Cntr=0.3,0.1

Type RM Length L Ch R = 1 ,19536   ,201,201,201
BEGIN DESCRIPTION:
Elm 02 05 19535.93
END DESCRIPTION:
XS GIS Cut Line= 4
      1595635.66      6820542.94      1595746.84      6820466.53
      1596028.95      6820463.01      1596617.02      6820423.95
#Sta/Elev= 30
  4582.9  1782.3  4615.3  1781.8  4621.3 1780.77  4630.2 1780.83  4636.2 1781.43
  4651.1  1781.4  4679.2  1780.8    4726 1780.84    4816 1779.83    4926 1779.19
    4986 1779.45  4995.5 1779.31    5006 1777.85  5022.5 1777.29    5023 1776.79
    5029 1776.79  5029.5 1777.29  5066.1 1779.27  5086.2 1778.93  5126.3 1780.71
  5166.4 1780.09  5196.4 1780.67  5276.6 1780.61  5301.7 1781.39  5306.7 1781.97
  5326.7 1782.05  5346.7 1781.35  5386.8 1781.75  5406.9 1781.36  5589.3 1781.36
#Mann= 3 ,-1 , 0
  4582.9     .05       0  5022.5     .05       0  5029.5     .05       0
Bank Sta=5022.5,5029.5
XS Rating Curve= 0 ,0
Exp/Cntr=0.3,0.1

Type RM Length L Ch R = 1 ,19335   ,477,477,477
BEGIN DESCRIPTION:
Elm 02 05 19334.9
END DESCRIPTION:
XS GIS Cut Line= 3
      1595683.88      6820656.15      1596107.07      6820634.45
      1596719.03      6820619.26
#Sta/Elev= 30
  4574.9 1780.52  4638.7 1780.83  4696.2 1780.07  4756.3 1780.21  4816.3 1778.75
  4856.4 1778.47  4906.5 1778.96  4926.5 1778.26  4946.5 1778.28  4956.5 1779.54
  4966.5 1779.67  4976.6 1778.92  4995.1  1776.6    5003 1776.28  5003.5 1775.78
  5009.6 1775.78  5010.1 1776.28  5016.6 1777.09  5036.6 1777.62  5066.6    1778
  5136.6 1777.84  5186.6    1779  5196.6 1779.66  5206.6 1779.23  5216.6 1779.86
  5286.7 1779.82  5326.7    1781  5346.7 1780.61  5516.7 1780.99  5610.8 1780.59
#Mann= 3 ,-1 , 0
  4574.9     .05       0    5003     .03       0  5010.1     .05       0
Bank Sta=5003,5010.1
XS Rating Curve= 0 ,0
Exp/Cntr=0.3,0.1

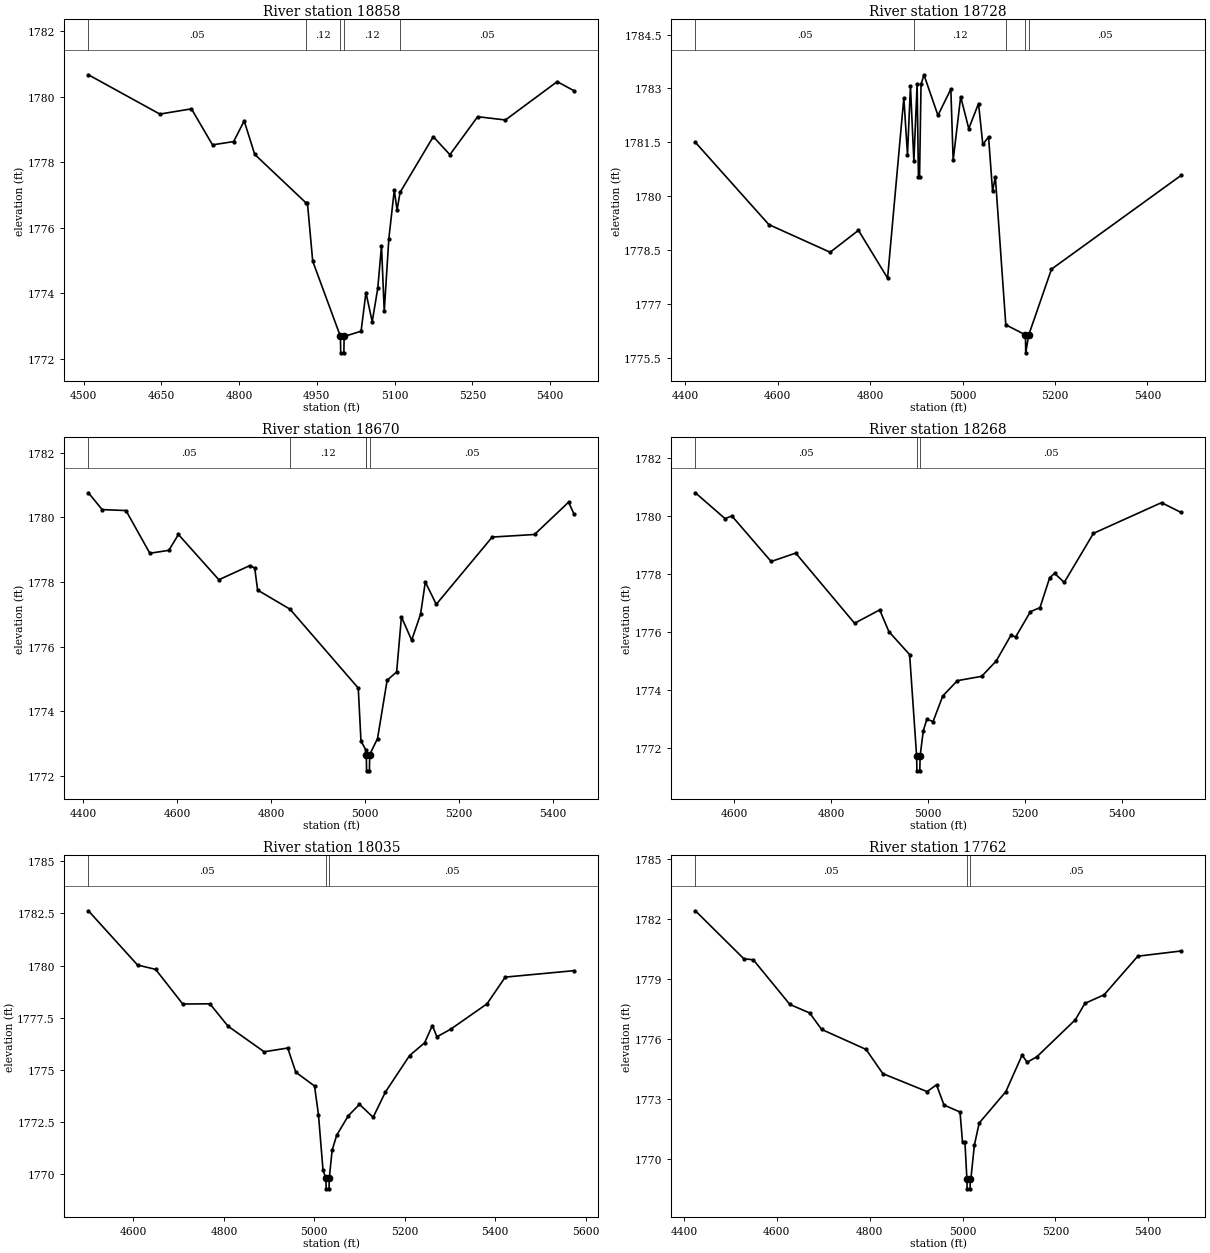
Type RM Length L Ch R = 1 ,18858   ,130,130,130
BEGIN DESCRIPTION:
Elm 02 05 18857.64
END DESCRIPTION:
XS GIS Cut Line= 3
      1595699.56      6820870.05       1596182.2      6820960.33
      1596598.83      6820800.62
#Sta/Elev= 30
  4509.2 1780.67    4647 1779.47    4708 1779.63  4748.7 1778.53  4789.4 1778.63
  4809.8 1779.26  4830.1 1778.24    4929 1776.76  4931.8 1776.75    4942 1774.98
  4995.5 1772.68    4996 1772.18  5002.1 1772.18  5002.6 1772.68  5035.3 1772.84
  5044.7 1774.02  5056.8 1773.13  5067.5 1774.15  5074.7 1775.45    5080 1773.45
  5088.9 1775.67  5099.4 1777.15  5104.7 1776.54  5110.6 1777.08  5174.6 1778.78
  5206.7 1778.23  5260.2 1779.39  5313.8 1779.29  5413.7 1780.46  5446.4 1780.18
#Mann= 5 ,-1 , 0
  4509.2     .05       0    4929     .12       0  4995.5     .07       0
  5002.6     .12       0  5110.6     .05       0
Bank Sta=4995.5,5002.6
XS Rating Curve= 0 ,0
Exp/Cntr=0.3,0.1

Type RM Length L Ch R = 1 ,18728   ,58,58,58
BEGIN DESCRIPTION:
Elm 02 05 18728.01
END DESCRIPTION:
XS GIS Cut Line= 6
      1595649.21       6820939.5      1596041.57      6821019.36
      1596093.65      6821083.59       1596187.4       6821069.7
      1596255.11       6821026.3      1596616.51      6820872.41
#Sta/Elev= 30
  4421.7  1781.5  4580.7 1779.21  4713.3 1778.44  4774.6 1779.05  4837.6 1777.72
  4872.8 1782.74  4880.7 1781.15  4887.1 1783.06  4894.5 1780.98  4901.5 1783.11
  4904.4 1780.54  4906.8 1780.54    4910 1783.11  4916.3 1783.38  4946.6 1782.25
  4974.5 1782.98  4979.5    1781  4995.8 1782.77  5013.3 1781.88  5034.4 1782.58
  5043.7 1781.44  5056.1 1781.65  5064.8 1780.14  5070.8 1780.54  5093.4 1776.42
    5136 1776.14  5136.5 1775.64  5143.1 1776.14  5192.3 1777.97  5472.8 1780.58
#Mann= 5 ,-1 , 0
  4421.7     .05       0  4894.5     .12       0  5093.4     .05       0
    5136     .07       0  5143.1     .05       0
Bank Sta=5136,5143.1
XS Rating Curve= 0 ,0
Exp/Cntr=0.3,0.1

Type RM Length L Ch R = 1 ,18670   ,402,402,402
BEGIN DESCRIPTION:
Elm 02 05 18669.77
END DESCRIPTION:
XS GIS Cut Line= 5
       1595656.2      6821043.67      1596012.06       6821107.9
      1596131.85      6821144.36       1596225.6      6821111.37
      1596666.59      6821028.03
#Sta/Elev= 30
  4410.5 1780.76  4439.8 1780.24  4490.6 1780.21  4541.4 1778.89    4582 1778.98
  4602.3 1779.47  4688.5 1778.07  4754.8 1778.51  4764.9 1778.43  4771.1 1777.75
    4840 1777.16  4985.5 1774.72  4991.3 1773.08  5001.5 1772.81  5002.7 1772.66
  5003.2 1772.16  5009.3 1772.16  5009.8 1772.66  5026.6 1773.16    5047 1774.96
  5067.3 1775.22  5077.5 1776.92  5099.3  1776.2  5118.2    1777  5128.4    1778
  5151.7 1777.31  5270.9 1779.39  5361.1 1779.47  5433.7 1780.47  5445.5 1780.09
#Mann= 5 ,-1 , 0
  4410.5     .05       0    4840     .12       0  5001.5     .05       0
  5002.7     .07       0  5009.8     .05       0
Bank Sta=5002.7,5009.8
XS Rating Curve= 0 ,0
Exp/Cntr=0.3,0.1

Type RM Length L Ch R = 1 ,18268   ,233,233,233
BEGIN DESCRIPTION:
Elm 02 05 18267.72
END DESCRIPTION:
XS GIS Cut Line= 3
      1595630.59       6821313.1      1596104.59       6821389.5
       1596625.4      6821347.83
#Sta/Elev= 30
  4520.1 1780.79  4581.3  1779.9  4595.5 1779.99  4676.5 1778.42  4727.2 1778.71
  4848.7 1776.29  4900.5 1776.75  4919.6    1776  4962.3 1775.21  4976.8  1771.7
  4977.3  1771.2  4983.4  1771.2  4983.9  1771.7  4990.5 1772.58  4997.9 1772.98
  5010.7  1772.9  5030.7 1773.78  5060.8 1774.31    5111 1774.46  5141.1 1774.99
  5171.2 1775.87  5181.2 1775.82  5211.7 1776.69  5231.4 1776.83  5251.4 1777.86
  5261.5 1778.01  5281.5  1777.7  5341.7 1779.39  5482.2 1780.45  5522.7 1780.11
#Mann= 3 ,-1 , 0
  4520.1     .05       0  4976.8     .05       0  4983.9     .05       0
Bank Sta=4976.8,4983.9
XS Rating Curve= 0 ,0
Exp/Cntr=0.3,0.1

Type RM Length L Ch R = 1 ,18035   ,273,273,273
BEGIN DESCRIPTION:
Elm 02 05 18034.96
END DESCRIPTION:
XS GIS Cut Line= 3
       1595606.3      6821629.08      1596106.33      6821622.13
      1596676.25      6821552.84
#Sta/Elev= 30
  4500.3 1782.63    4609 1780.03    4649 1779.82    4709 1778.16    4769 1778.17
    4809  1777.1    4889 1775.87  4941.1 1776.05    4959 1774.89  5000.4 1774.23
  5009.1 1772.85  5019.2 1770.18  5025.6  1769.8  5026.1  1769.3  5032.4  1769.3
  5032.9  1769.8  5039.3 1771.15  5049.4 1771.87  5075.3 1772.81  5099.8 1773.35
    5130 1772.73  5157.1 1773.94  5210.6 1775.69  5243.8  1776.3    5261 1777.13
    5271 1776.59  5301.3 1776.95  5381.8 1778.17  5422.1 1779.45  5574.5 1779.76
#Mann= 3 ,-1 , 0
  4500.3     .05       0  5025.6     .05       0  5032.9     .05       0
Bank Sta=5025.6,5032.9
XS Rating Curve= 0 ,0
Exp/Cntr=0.3,0.1

Type RM Length L Ch R = 1 ,17762   ,366,366,366
BEGIN DESCRIPTION:
Elm 02 05 17762.04
END DESCRIPTION:
XS GIS Cut Line= 3
      1595691.79      6821924.27      1596260.76      6821837.04
      1596715.18      6821715.94
#Sta/Elev= 30
  4424.8 1782.43  4529.2 1780.03  4549.5 1779.98  4628.2 1777.75  4670.9 1777.32
  4696.6  1776.5  4792.3  1775.5  4828.4 1774.29  4923.8 1773.39    4944 1773.73
  4960.1 1772.72  4994.6 1772.37    5000 1770.87  5005.2 1770.87  5009.4 1769.03
  5009.9 1768.53  5016.2 1768.53  5016.7 1769.03  5018.2 1769.07  5025.5 1770.71
  5035.9 1771.82  5093.3 1773.39  5128.2 1775.21  5139.3 1774.86    5160 1775.13
  5242.8 1776.98  5263.5  1777.8  5304.9 1778.23  5377.4 1780.16  5470.7 1780.42
#Mann= 3 ,-1 , 0
  4424.8     .05       0  5009.4     .05       0  5016.7     .05       0
Bank Sta=5009.4,5016.7
XS Rating Curve= 0 ,0
Exp/Cntr=0.3,0.1

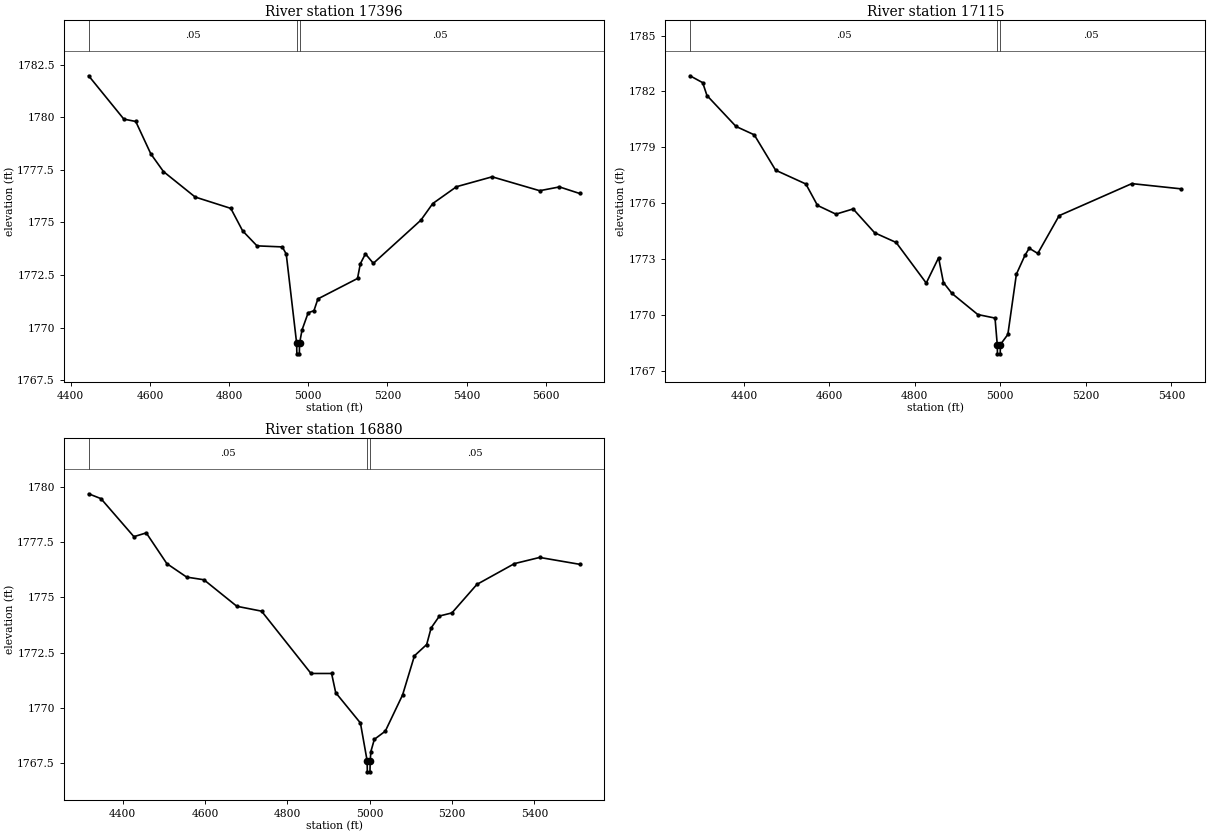
Type RM Length L Ch R = 1 ,17396   ,281,281,281
BEGIN DESCRIPTION:
Elm 02 05 17395.56
END DESCRIPTION:
XS GIS Cut Line= 3
      1595706.09      6822116.99      1596260.76      6822137.82
      1596945.66      6822113.08
#Sta/Elev= 30
  4445.1 1781.97  4534.1 1779.91  4564.1  1779.8  4602.2 1778.26  4634.1 1777.42
  4714.2 1776.21  4804.3 1775.67  4834.3  1774.6  4870.5 1773.89  4934.4 1773.84
  4944.4  1773.5  4970.7 1769.26  4971.2 1768.76  4977.5 1768.76    4978 1769.26
  4984.4  1769.9  4999.8 1770.71  5014.4 1770.81  5024.4 1771.37  5124.5 1772.34
  5131.6 1773.04  5144.5 1773.51  5164.5 1773.06  5284.6 1775.11  5314.6  1775.9
  5374.6  1776.7  5464.7 1777.17  5584.8 1776.51  5634.8 1776.69  5685.5 1776.38
#Mann= 3 ,-1 , 0
  4445.1     .05       0  4970.7     .05       0    4978     .05       0
Bank Sta=4970.7,4978
XS Rating Curve= 0 ,0
Exp/Cntr=0.3,0.1

Type RM Length L Ch R = 1 ,17115   ,235,235,235
BEGIN DESCRIPTION:
Elm 02 05 17115.32
END DESCRIPTION:
XS GIS Cut Line= 3
      1595625.51      6822311.43      1596347.74      6822387.82
      1596769.64      6822382.61
#Sta/Elev= 30
  4274.1 1782.84  4303.8 1782.47  4313.8 1781.78  4381.7 1780.12  4424.4 1779.67
  4474.4 1777.77  4545.1 1777.03  4572.3 1775.88  4615.5 1775.41  4655.7 1775.69
    4706 1774.41  4756.3 1773.89  4826.7 1771.71  4855.6 1773.07  4866.9 1771.74
    4887 1771.15  4947.3 1770.02  4987.6 1769.83  4992.8 1768.41  4993.3 1767.91
  4999.7 1767.91  5000.2 1768.41  5017.6 1768.95  5037.6 1772.19  5057.6  1773.2
  5067.6 1773.58  5087.6  1773.3  5137.6 1775.33  5307.6 1777.05  5422.3 1776.77
#Mann= 3 ,-1 , 0
  4274.1     .05       0  4992.8     .05       0  5000.2     .05       0
Bank Sta=4992.8,5000.2
XS Rating Curve= 0 ,0
Exp/Cntr=0.3,0.1

Type RM Length L Ch R = 1 ,16880   ,268,268,268
BEGIN DESCRIPTION:
Elm 02 05 16880.38
END DESCRIPTION:
XS GIS Cut Line= 3
      1595615.15      6822597.89      1596300.87        6822584.
      1596801.34       6822507.8
#Sta/Elev= 30
  4317.5 1779.69  4347.4 1779.47  4427.4 1777.75  4457.4 1777.92  4507.4 1776.53
  4555.6 1775.92  4597.4  1775.8  4677.4  1774.6  4737.4 1774.38  4857.5 1771.56
  4907.5 1771.56  4917.5 1770.69  4977.5 1769.32  4993.8 1767.61  4994.3 1767.11
  5000.7 1767.11  5001.2 1767.61  5002.9 1768.03  5011.3 1768.58  5037.9 1768.95
  5079.9 1770.59  5108.7 1772.36  5138.4 1772.87  5149.2 1773.62  5169.4 1774.16
  5199.7  1774.3  5260.4 1775.59  5351.5 1776.53  5412.9 1776.81  5509.6  1776.5
#Mann= 3 ,-1 , 0
  4317.5     .05       0  4993.8     .05       0  5001.2     .05       0
Bank Sta=4993.8,5001.2
XS Rating Curve= 0 ,0
Exp/Cntr=0.3,0.1