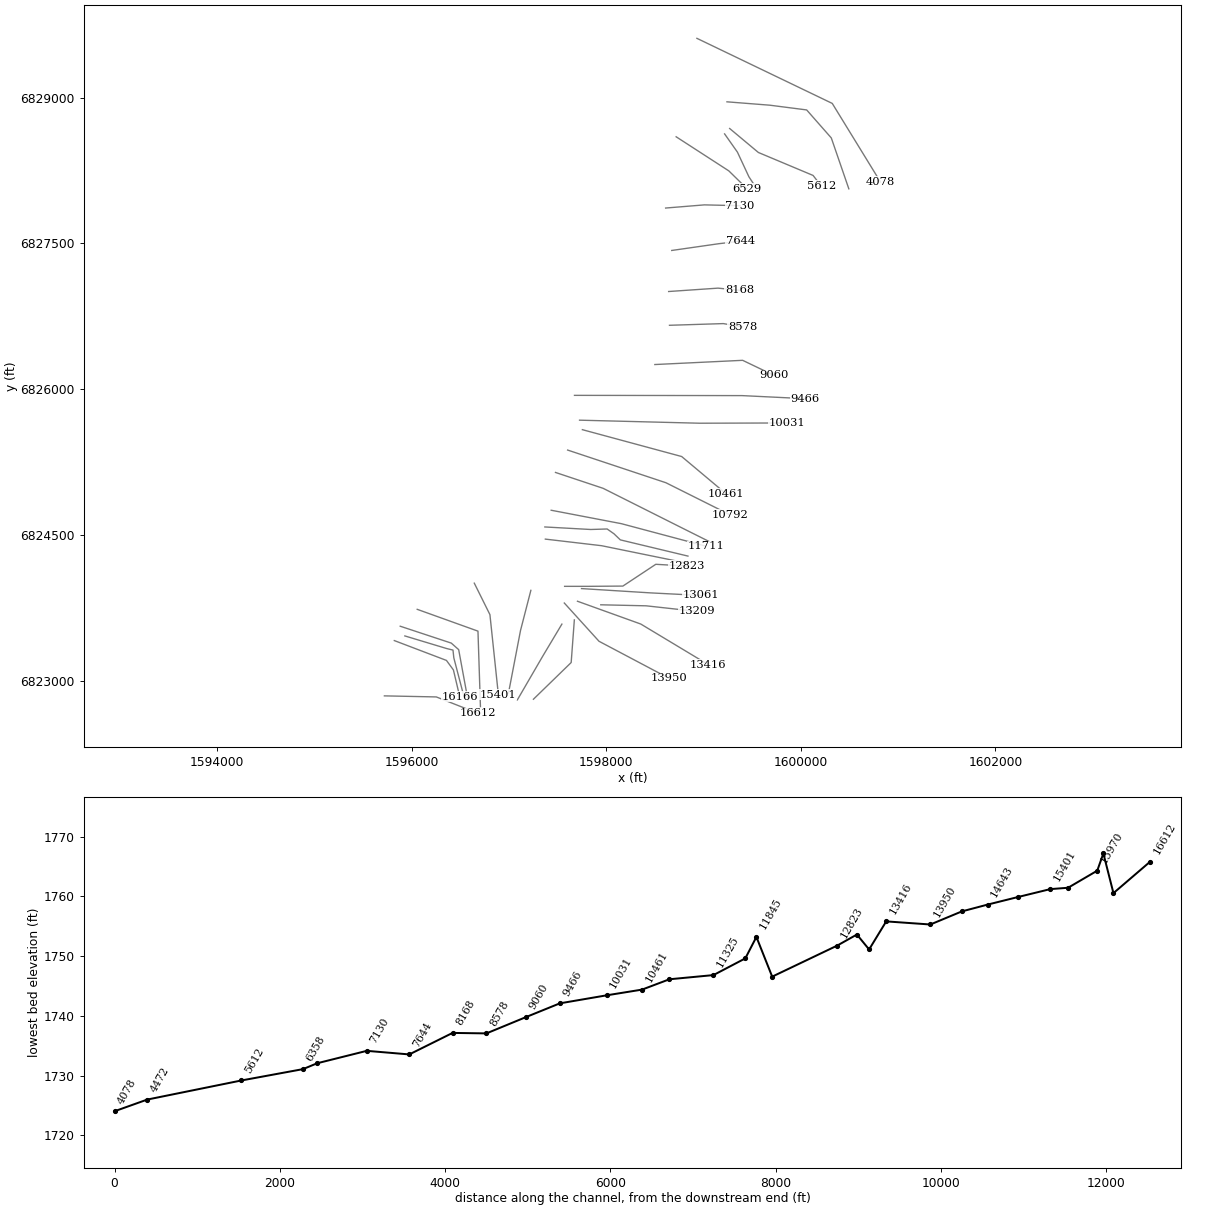
HEC-RAS study Elm 02 05.prj: Elm 02 05 Base Level Engineering

--- Elm 02 05.g01 (geometry) --- (continued)

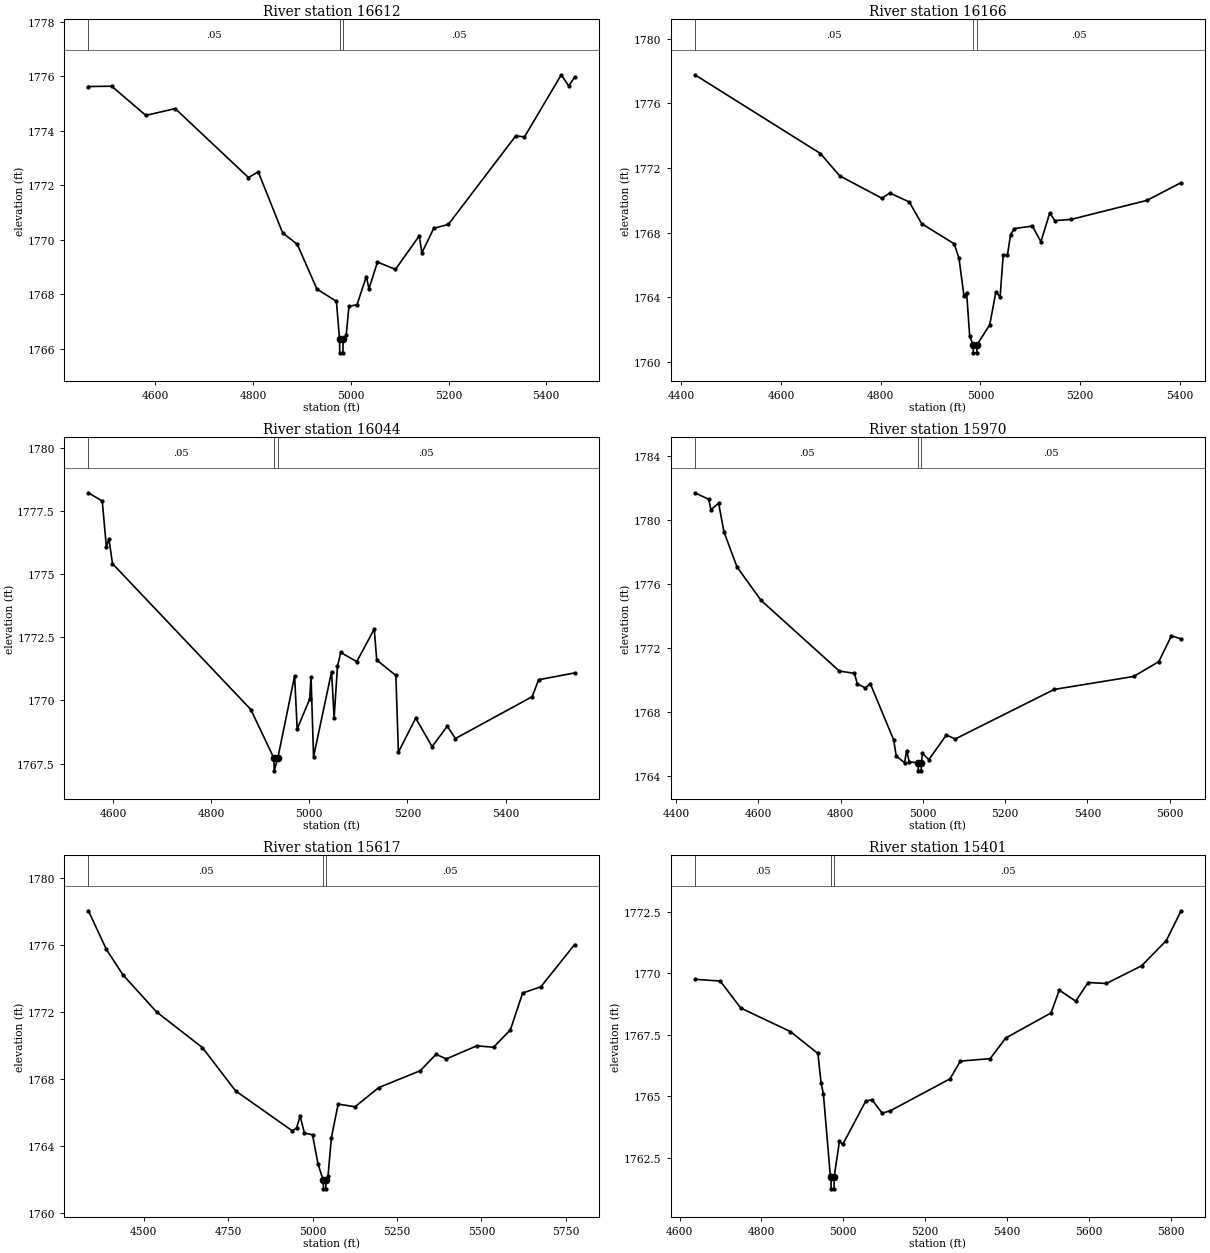
Type RM Length L Ch R = 1 ,16612   ,446,446,446
BEGIN DESCRIPTION:
Elm 02 05 16611.5
END DESCRIPTION:
XS GIS Cut Line= 3
      1595717.44      6822848.18       1596251.3      6822837.33
      1596680.52      6822668.24
#Sta/Elev= 30
  4462.9 1775.62  4510.5 1775.63  4580.5 1774.56  4640.5 1774.81  4790.5 1772.28
  4810.5 1772.49  4860.5 1770.25  4890.5 1769.83  4930.6 1768.19  4970.6 1767.74
  4976.9 1766.35  4977.4 1765.85  4983.8 1765.85  4984.3 1766.35  4990.6  1766.5
  4996.2 1767.55  5012.8 1767.62  5031.8 1768.65  5037.2  1768.2  5054.6 1769.18
  5091.4 1768.91  5140.1 1770.14  5145.5 1769.52  5169.9 1770.42  5199.7 1770.56
  5337.7 1773.81  5355.5 1773.77  5430.8 1776.05    5446 1775.64  5458.2 1775.96
#Mann= 3 ,-1 , 0
  4462.9     .05       0  4976.9     .05       0  4984.3     .05       0
Bank Sta=4976.9,4984.3
XS Rating Curve= 0 ,0
Exp/Cntr=0.3,0.1

Type RM Length L Ch R = 1 ,16166   ,122,122,122
BEGIN DESCRIPTION:
Elm 02 05 16165.88
END DESCRIPTION:
XS GIS Cut Line= 4
      1595819.45      6823416.75      1596355.47      6823212.76
      1596427.08       6823115.1      1596491.77      6822841.26
#Sta/Elev= 30
  4426.9 1777.76  4678.9 1772.89  4717.5 1771.51  4802.5 1770.12    4818 1770.45
  4857.3 1769.89  4882.1 1768.55  4947.6  1767.3  4957.1  1766.4    4967 1764.08
  4972.4 1764.28  4978.5 1761.59  4985.3 1761.06  4985.8 1760.56  4992.7 1760.56
  4993.2 1761.06  5018.7 1762.29  5031.2 1764.34  5039.6 1764.01  5045.8 1766.63
  5054.3  1766.6  5060.5 1767.87  5068.3 1768.25  5104.4  1768.4  5121.5 1767.43
  5139.2 1769.21  5149.4 1768.74  5181.5 1768.81  5334.3 1769.99  5402.9 1771.09
#Mann= 3 ,-1 , 0
  4426.9     .05       0  4985.3     .05       0  4993.2     .05       0
Bank Sta=4985.3,4993.2
XS Rating Curve= 0 ,0
Exp/Cntr=0.3,0.1

Type RM Length L Ch R = 1 ,16044   ,74,74,74
BEGIN DESCRIPTION:
Elm 02 05 16043.85
END DESCRIPTION:
XS GIS Cut Line= 5
      1595927.97      6823464.49      1596359.81      6823334.29
      1596422.74       6823319.1      1596431.42       6823238.8
      1596531.25      6822856.87
#Sta/Elev= 30
  4549.6 1778.23  4577.8  1777.9  4586.2 1776.09  4591.4  1776.4  4598.7 1775.42
  4880.7 1769.64  4927.8 1767.71  4928.3 1767.21  4935.7 1767.71    4970 1770.97
  4975.2 1768.87  5000.6 1770.05  5003.5 1770.93  5008.6 1767.77  5045.4 1771.14
  5050.5 1769.31  5057.4 1771.35    5064  1771.9  5096.7 1771.54  5132.4 1772.83
  5137.4  1771.6  5176.4 1770.99  5181.6 1767.95  5216.9  1769.3  5250.3 1768.17
  5281.3 1768.98  5297.8 1768.49  5454.4 1770.15  5467.4 1770.82  5540.9 1771.09
#Mann= 3 ,-1 , 0
  4549.6     .05       0  4927.8     .05       0  4935.7     .05       0
Bank Sta=4927.8,4935.7
XS Rating Curve= 0 ,0
Exp/Cntr=0.3,0.1

Type RM Length L Ch R = 1 ,15970   ,353,353,353
BEGIN DESCRIPTION:
Elm 02 05 15970.24
END DESCRIPTION:
XS GIS Cut Line= 4
      1595880.19      6823564.33      1596405.38      6823390.71
      1596481.34      6823323.44      1596576.82      6822804.76
#Sta/Elev= 30
  4445.7  1781.7  4479.4 1781.29  4484.7 1780.64  4503.4 1781.05  4516.4 1779.25
  4548.2 1777.06  4606.4 1774.98  4796.7 1770.56  4833.7 1770.41  4840.5 1769.76
  4860.2  1769.5  4872.1 1769.77  4928.9 1766.26  4935.2 1765.24  4955.4 1764.83
  4960.6 1765.58  4966.8 1764.88  4988.4 1764.82  4988.9 1764.32  4995.8 1764.32
  4996.3 1764.82  4998.8 1765.41  5014.4 1765.02  5057.1 1766.56  5078.5 1766.31
  5319.4 1769.41  5512.6 1770.22  5573.6 1771.15  5604.1 1772.76  5627.7 1772.57
#Mann= 3 ,-1 , 0
  4445.7     .05       0  4988.4     .05       0  4996.3     .05       0
Bank Sta=4988.4,4996.3
XS Rating Curve= 0 ,0
Exp/Cntr=0.3,0.1

Type RM Length L Ch R = 1 ,15617   ,216,216,216
BEGIN DESCRIPTION:
Elm 02 05 15617.135
END DESCRIPTION:
XS GIS Cut Line= 3
      1596054.98      6823738.01      1596679.63      6823513.73
        1596705.      6822738.04
#Sta/Elev= 30
  4336.3 1778.03  4389.4 1775.73  4438.6 1774.21  4538.2    1772  4673.8 1769.88
    4772  1767.3  4939.8 1764.92  4952.6 1765.08  4963.2  1765.8  4975.8 1764.79
    5000 1764.68    5016 1762.95  5031.8 1761.96  5032.3 1761.46  5039.2 1761.46
  5039.7 1761.96  5045.8 1762.21  5055.8 1764.51  5075.8 1766.51  5125.8 1766.35
  5195.8 1767.49    5319  1768.5  5365.9 1769.48  5395.9  1769.2    5486 1769.98
    5536  1769.9    5586 1770.94  5622.1 1773.13  5676.1  1773.5  5776.1 1776.02
#Mann= 3 ,-1 , 0
  4336.3     .05       0  5031.8     .05       0  5039.7     .05       0
Bank Sta=5031.8,5039.7
XS Rating Curve= 0 ,0
Exp/Cntr=0.3,0.1

Type RM Length L Ch R = 1 ,15401   ,396,396,396
BEGIN DESCRIPTION:
Elm 02 05 15401.32
END DESCRIPTION:
XS GIS Cut Line= 3
      1596641.91      6824007.06      1596802.52      6823683.68
      1596889.23      6822862.11
#Sta/Elev= 30
  4637.5 1769.76  4699.3 1769.69  4749.6 1768.59  4870.9 1767.63  4937.9 1766.74
  4945.7 1765.53  4951.3 1765.09  4968.1 1761.78  4969.8 1761.73  4970.3 1761.23
  4977.2 1761.23  4977.7 1761.73  4990.5 1763.17  4998.6 1763.04  5054.6  1764.8
  5069.8 1764.86  5094.8 1764.31  5114.9 1764.41  5260.6 1765.71  5285.8 1766.43
  5358.5 1766.53  5396.4 1767.37  5507.1 1768.39  5527.2 1769.32  5567.4 1768.87
  5597.6 1769.63  5642.2 1769.59  5728.3 1770.31  5788.6 1771.34  5824.7 1772.55
#Mann= 3 ,-1 , 0
  4637.5     .05       0  4969.8     .05       0  4977.7     .05       0
Bank Sta=4969.8,4977.7
XS Rating Curve= 0 ,0
Exp/Cntr=0.3,0.1

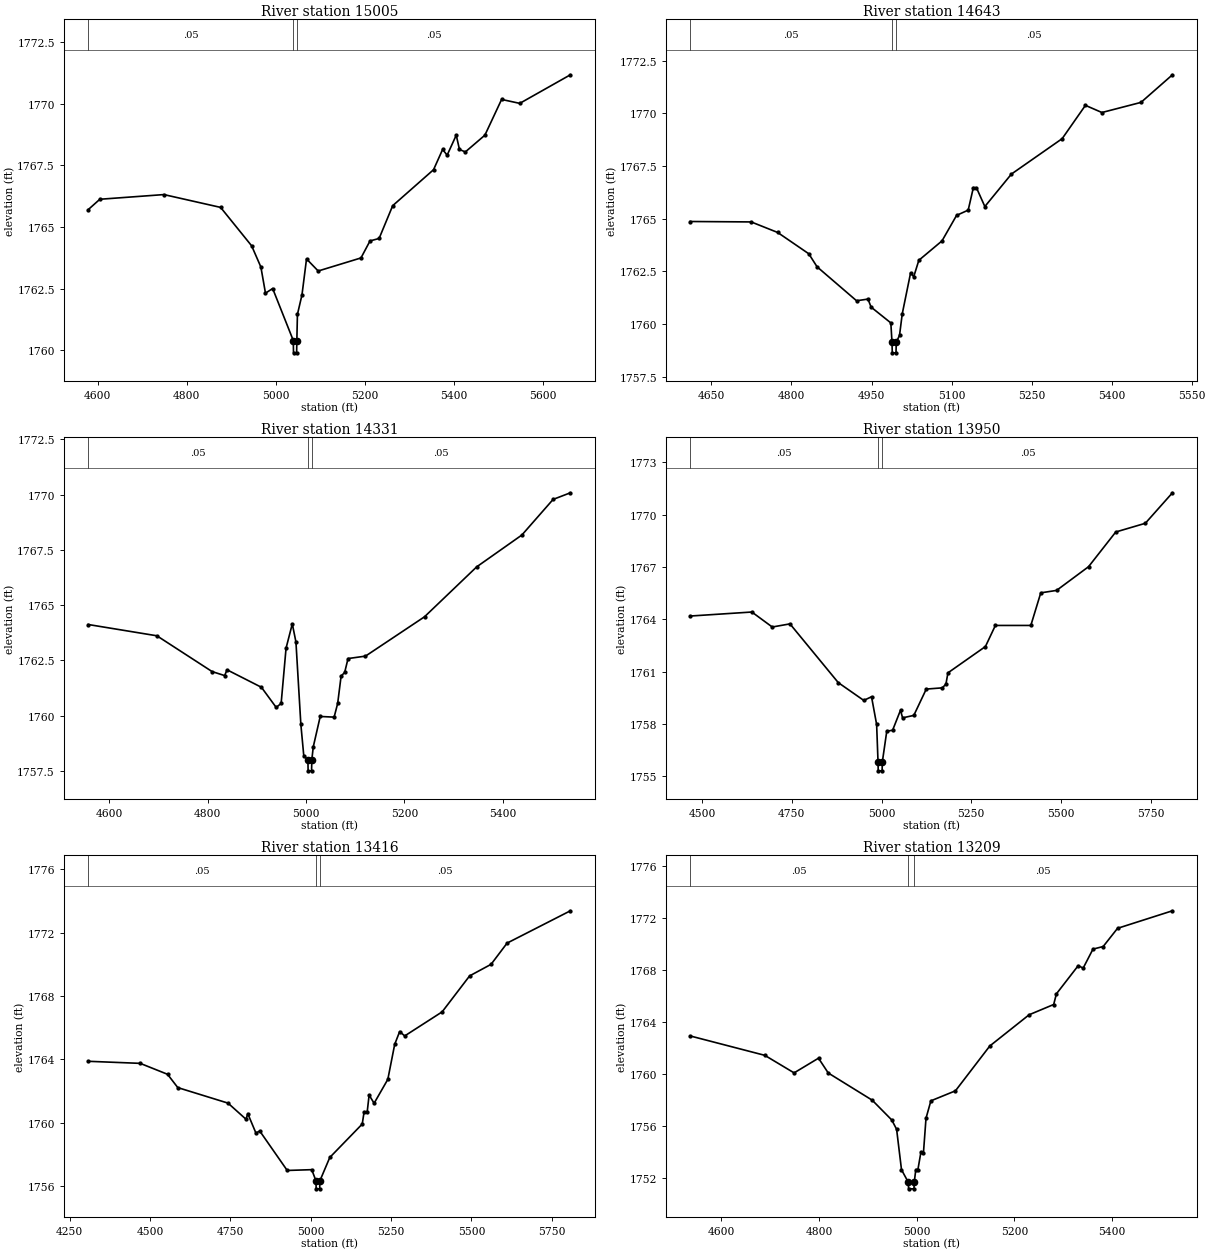
Type RM Length L Ch R = 1 ,15005   ,362,362,362
BEGIN DESCRIPTION:
Elm 02 05 15005.24
END DESCRIPTION:
XS GIS Cut Line= 3
      1597223.52      6823933.22      1597117.19      6823520.92
      1596993.49      6822876.38
#Sta/Elev= 30
  4579.1  1765.7  4605.2 1766.12    4749 1766.31  4876.2 1765.79  4945.9 1764.23
  4966.6 1763.37  4976.9 1762.31    4993  1762.5  5039.3 1760.39  5039.8 1759.89
  5046.8 1759.89  5047.3 1760.39  5048.6 1761.45  5058.8 1762.24    5069  1763.7
  5095.2 1763.21  5191.2 1763.74  5211.5 1764.43  5231.9 1764.53  5262.4 1765.86
  5354.1 1767.32  5374.4 1768.14  5384.6 1767.91    5405 1768.72  5412.2 1768.14
  5425.4 1768.04  5469.3 1768.72  5506.8 1770.17  5547.5 1770.01  5661.2 1771.17
#Mann= 3 ,-1 , 0
  4579.1     .05       0  5039.3     .05       0  5047.3     .05       0
Bank Sta=5039.3,5047.3
XS Rating Curve= 0 ,0
Exp/Cntr=0.3,0.1

Type RM Length L Ch R = 1 ,14643   ,312,312,312
BEGIN DESCRIPTION:
Elm 02 05 14643.27
END DESCRIPTION:
XS GIS Cut Line= 3
      1597542.54      6823586.03      1597342.88      6823251.82
      1597084.64      6822806.95
#Sta/Elev= 30
  4610.3 1764.87  4724.5 1764.85  4774.1 1764.35  4832.4 1763.34    4848 1762.72
    4922 1761.11  4943.4 1761.19  4949.2 1760.81  4986.2 1760.06  4988.4 1759.14
  4988.9 1758.64  4995.9 1758.64  4996.4 1759.14  5002.5 1759.47  5007.6 1760.49
  5023.3 1762.44  5029.1 1762.25  5038.7 1763.03  5082.1 1763.95  5109.4 1765.16
  5131.2 1765.41  5140.9 1766.48  5146.7 1766.47  5162.4 1765.58  5212.2 1767.12
  5307.3  1768.8  5350.9 1770.38  5381.8 1770.04    5455 1770.52    5514 1771.83
#Mann= 3 ,-1 , 0
  4610.3     .05       0  4988.4     .05       0  4996.4     .05       0
Bank Sta=4988.4,4996.4
XS Rating Curve= 0 ,0
Exp/Cntr=0.3,0.1

Type RM Length L Ch R = 1 ,14331   ,381,381,381
BEGIN DESCRIPTION:
Elm 02 05 14331.2
END DESCRIPTION:
XS GIS Cut Line= 3
      1597670.57       6823629.4      1597638.02      6823191.06
      1597249.77      6822813.65
#Sta/Elev= 30
  4556.9 1764.12  4696.6 1763.61    4809 1761.99  4834.4 1761.81  4839.4 1762.07
  4909.3 1761.28  4939.3 1760.37  4949.4 1760.55  4959.4 1763.05  4972.1 1764.15
  4979.5 1763.33  4989.5  1759.6  4995.5 1758.17  5003.8    1758  5004.3  1757.5
  5011.3  1757.5  5011.8    1758  5014.8 1758.59  5028.9 1759.96  5057.2 1759.93
  5064.4 1760.55  5071.4 1761.79  5078.6 1761.95  5085.5 1762.58    5121 1762.69
  5241.1 1764.47  5347.3 1766.73  5439.2 1768.17  5502.7 1769.78  5537.9 1770.08
#Mann= 3 ,-1 , 0
  4556.9     .05       0  5003.8     .05       0  5011.8     .05       0
Bank Sta=5003.8,5011.8
XS Rating Curve= 0 ,0
Exp/Cntr=0.3,0.1

Type RM Length L Ch R = 1 ,13950   ,534,534,534
BEGIN DESCRIPTION:
Elm 02 05 13949.53
END DESCRIPTION:
XS GIS Cut Line= 3
      1597567.36       6823802.9      1597924.15      6823409.65
      1598641.49      6823030.19
#Sta/Elev= 30
  4467.5 1764.19    4639 1764.42  4695.8 1763.56  4745.1 1763.74  4879.6 1760.37
  4950.6 1759.35  4972.2 1759.56  4986.4 1757.97  4990.3 1755.81  4990.8 1755.31
  5001.7 1755.31  5002.2 1755.81  5014.6 1757.58  5030.9 1757.64  5052.9 1758.79
  5058.6 1758.35  5089.9 1758.49  5124.6    1760  5169.1 1760.07  5179.3 1760.28
  5184.9 1760.93  5289.3 1762.44    5317 1763.65  5415.7 1763.65  5443.4 1765.52
  5487.4 1765.66  5576.4 1767.02  5652.1 1769.01  5734.5 1769.51    5810 1771.26
#Mann= 3 ,-1 , 0
  4467.5     .05       0  4990.3     .05       0  5002.2     .05       0
Bank Sta=4990.3,5002.2
XS Rating Curve= 0 ,0
Exp/Cntr=0.3,0.1

Type RM Length L Ch R = 1 ,13416   ,207,207,207
BEGIN DESCRIPTION:
Elm 02 05 13415.63
END DESCRIPTION:
XS GIS Cut Line= 3
      1597702.82       6823821.1      1598353.84      6823586.73
      1599046.56      6823170.06
#Sta/Elev= 30
  4307.7 1763.88  4469.4 1763.75  4554.5 1763.06  4586.4 1762.22  4742.7 1761.24
  4798.8 1760.22  4804.1 1760.58  4829.5 1759.35  4841.4 1759.48  4926.9 1756.99
  5003.2 1757.04  5016.4 1756.33  5016.9 1755.83  5027.9 1755.83  5028.4 1756.33
  5059.3 1757.81  5160.3 1759.92  5166.1 1760.69  5175.8  1760.7  5181.7 1761.75
  5197.2 1761.23  5239.9 1762.74  5261.3 1764.95  5276.8 1765.76  5292.4 1765.48
  5408.9    1767  5494.4 1769.27  5561.1    1770    5611 1771.34    5808 1773.38
#Mann= 3 ,-1 , 0
  4307.7     .05       0  5016.4     .05       0  5028.4     .05       0
Bank Sta=5016.4,5028.4
XS Rating Curve= 0 ,0
Exp/Cntr=0.3,0.1

Type RM Length L Ch R = 1 ,13209   ,148,148,148
BEGIN DESCRIPTION:
Elm 02 05 13209.34
END DESCRIPTION:
XS GIS Cut Line= 3
      1597942.36      6823784.65      1598408.53      6823774.23
      1598926.79      6823716.93
#Sta/Elev= 30
  4536.2 1762.89  4688.9  1761.4  4748.9 1760.05  4798.9 1761.18  4818.9 1760.04
  4908.9 1757.95  4948.9 1756.43  4958.9 1755.71  4968.9  1752.6  4982.9 1751.63
  4983.4 1751.13  4994.5 1751.13    4995 1751.63  4998.2 1752.61  5002.5 1752.61
  5008.8 1753.98  5013.8 1753.87  5019.1 1756.56  5029.1  1757.9  5079.4 1758.67
  5149.8 1762.12  5230.3 1764.52  5280.6 1765.31  5286.2 1766.13  5330.9  1768.3
    5341 1768.11  5361.1 1769.57    5382 1769.77  5411.4 1771.17  5523.9 1772.52
#Mann= 3 ,-1 , 0
  4536.2     .05       0  4982.9     .05       0    4995     .05       0
Bank Sta=4982.9,4995
XS Rating Curve= 0 ,0
Exp/Cntr=0.3,0.1

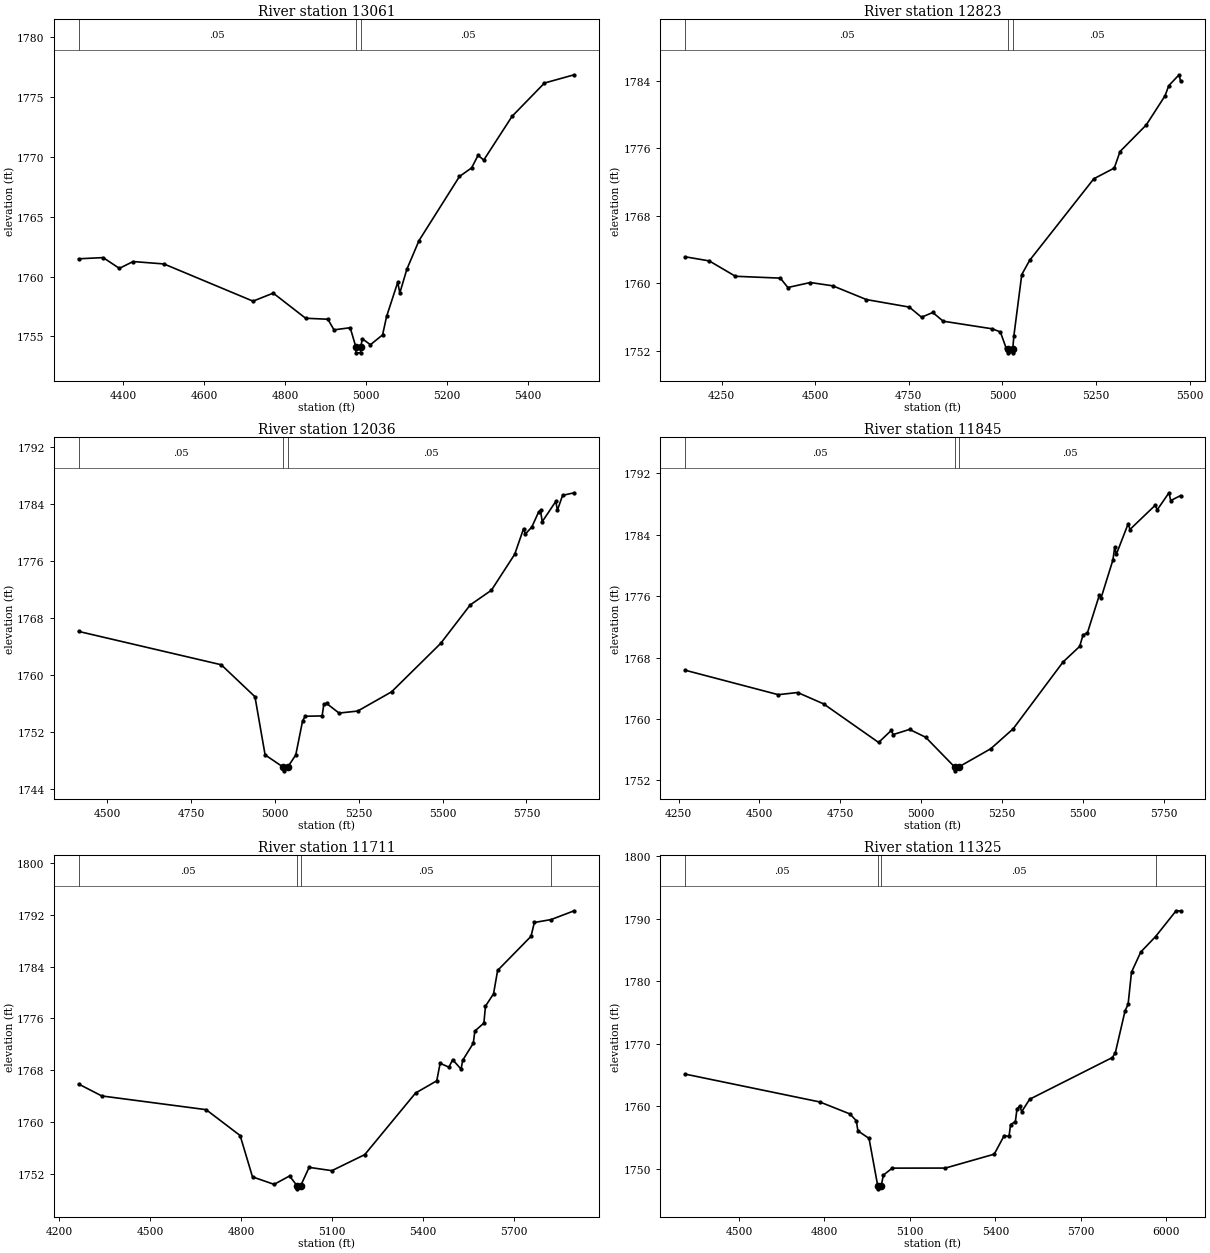
Type RM Length L Ch R = 1 ,13061   ,238,238,238
BEGIN DESCRIPTION:
Elm 02 05 13060.86
END DESCRIPTION:
XS GIS Cut Line= 3
      1597744.45      6823951.31       1598455.4      6823907.04
      1598968.41        6823881.
#Sta/Elev= 30
  4289.3 1761.49    4350 1761.59    4390 1760.69  4424.1 1761.26  4500.3 1761.06
  4720.7 1757.95  4770.8 1758.62  4850.9 1756.52  4905.9 1756.44  4921.1 1755.55
  4961.2 1755.73  4975.1 1754.13  4975.6 1753.63  4986.8 1753.63  4987.3 1754.13
  4991.2  1754.8  5011.2 1754.31  5041.3 1755.13  5051.3 1756.68  5078.8 1759.53
  5083.9 1758.63  5101.4 1760.62  5131.4 1763.01  5231.5 1768.37  5261.6 1769.09
  5277.6 1770.14  5291.6 1769.74  5361.7  1773.4  5441.8 1776.18  5515.3 1776.87
#Mann= 3 ,-1 , 0
  4289.3     .05       0  4975.1     .05       0  4987.3     .05       0
Bank Sta=4975.1,4987.3
XS Rating Curve= 0 ,0
Exp/Cntr=0.3,0.1

Type RM Length L Ch R = 1 ,12823   ,787,787,787
BEGIN DESCRIPTION:
Mapping XS 470637d0
END DESCRIPTION:
XS GIS Cut Line= 5
      1597570.53      6823974.47      1597815.31      6823974.47
      1598169.48      6823977.08      1598508.02      6824201.03
      1598826.63       6824182.9
#Sta/Elev= 30
  4152.2 1763.16  4216.7 1762.67  4286.7 1760.85  4406.7 1760.63  4426.7 1759.52
  4486.7 1760.11  4546.7 1759.72  4636.7 1758.09  4751.2  1757.2  4783.9    1756
    4814 1756.56  4841.7 1755.53  4973.5 1754.62  4994.6 1754.25  5009.6 1752.39
  5015.5 1752.28    5016 1751.78  5027.2 1751.78  5027.7 1752.28  5030.7 1753.81
  5051.7 1761.05  5072.8 1762.74  5244.2  1772.4  5298.9 1773.67  5314.3 1775.63
  5384.4 1778.78  5434.5 1782.23  5444.5 1783.43    5472 1784.72  5476.2 1783.93
#Mann= 3 ,-1 , 0
  4152.2     .05       0  5015.5     .05       0  5027.7     .05       0
Bank Sta=5015.5,5027.7
XS Rating Curve= 0 ,0
Exp/Cntr=0.3,0.1

Type RM Length L Ch R = 1 ,12036   ,191,191,191
BEGIN DESCRIPTION:
Elm 02 05 12036.41
END DESCRIPTION:
XS GIS Cut Line= 3
      1597372.49      6824459.99      1597950.63      6824392.28
      1598828.83      6824213.01
#Sta/Elev= 30
    4414 1766.15  4839.4 1761.47  4940.1 1756.98  4970.3 1748.82    5025 1747.08
  5025.5 1746.58  5037.4 1747.08  5061.8 1748.81  5082.2  1753.6  5089.9 1754.24
  5140.4 1754.29  5145.5 1755.91  5153.6 1756.05  5190.9 1754.69  5246.5 1754.97
  5347.6 1757.67    5494 1764.46  5582.3 1769.87  5645.5 1771.93    5715 1776.98
  5741.5 1780.58  5746.6 1779.81    5766  1780.8  5786.4 1782.92    5792 1783.13
  5797.1 1781.55  5837.4 1784.39  5842.5 1783.18  5857.9 1785.25  5892.4 1785.61
#Mann= 3 ,-1 , 0
    4414     .05       0    5025     .05       0  5037.4     .05       0
Bank Sta=5025,5037.4
XS Rating Curve= 0 ,0
Exp/Cntr=0.3,0.1

Type RM Length L Ch R = 1 ,11845   ,134,134,134
BEGIN DESCRIPTION:
Elm 02 05 11844.16
END DESCRIPTION:
XS GIS Cut Line= 6
       1597367.3      6824584.99      1597838.65      6824558.95
      1598007.92      6824564.16      1598078.23      6824514.68
      1598143.34      6824452.18      1598838.69       6824285.5
#Sta/Elev= 30
  4270.1 1766.35  4558.2 1763.16  4618.3 1763.44  4698.5 1761.96  4868.6 1756.93
  4907.6 1758.49  4913.8 1757.96  4964.3 1758.63  5014.1 1757.61  5103.8 1753.73
  5104.3 1753.23  5116.2 1753.73  5215.5 1756.11  5284.8 1758.71  5439.1 1767.42
  5490.5 1769.45  5500.8 1770.93  5514.7 1771.25  5551.6 1776.17  5556.7 1775.77
  5593.3 1780.71  5598.8 1782.38  5603.9 1781.46  5640.8 1785.47  5645.9 1784.69
  5724.8 1787.88    5730 1787.24  5766.8 1789.48    5772 1788.46  5802.8 1789.12
#Mann= 3 ,-1 , 0
  4270.1     .05       0  5103.8     .05       0  5116.2     .05       0
Bank Sta=5103.8,5116.2
XS Rating Curve= 0 ,0
Exp/Cntr=0.3,0.1

Type RM Length L Ch R = 1 ,11711   ,386,386,386
BEGIN DESCRIPTION:
Elm 02 05 11710.74
END DESCRIPTION:
XS GIS Cut Line= 3
      1597432.35      6824756.88      1598153.75      6824618.85
      1599021.78      6824387.55
#Sta/Elev= 30
  4264.7 1765.84  4341.1    1764  4684.8 1761.88  4796.8 1757.88  4837.6 1751.49
  4908.8 1750.33  4959.7 1751.63  4984.1 1750.14  4984.6 1749.64  4996.5 1750.14
  5024.1 1752.96  5099.2 1752.45  5207.5 1754.93  5374.8 1764.45  5444.7 1766.34
  5455.8 1769.05  5484.8 1768.45  5497.2 1769.61  5524.9 1768.14  5530.1 1769.51
  5565.1 1772.15  5570.2 1774.04    5600 1775.26  5605.2 1777.88  5631.8 1779.79
  5645.3 1783.41  5755.3 1788.68  5766.3 1790.82  5821.4 1791.27  5897.5 1792.63
#Mann= 4 ,-1 , 0
  4264.7     .05       0  4984.1     .05       0  4996.5     .05       0
  5821.4     .12       0
Bank Sta=4984.1,4996.5
XS Rating Curve= 0 ,0
Exp/Cntr=0.3,0.1

Type RM Length L Ch R = 1 ,11325   ,533,533,533
BEGIN DESCRIPTION:
Mapping XS 11757887
END DESCRIPTION:
XS GIS Cut Line= 4
      1597476.76      6825145.48      1597966.35      6824982.28
       1598810.1      6824558.67      1599060.01      6824433.72
#Sta/Elev= 30
  4310.8 1765.18  4783.3 1760.73  4889.5 1758.81  4911.9 1757.72  4917.4 1756.11
  4956.5  1754.9    4987 1747.34  4987.5 1746.84  4999.4 1747.34  5006.8 1749.03
    5038 1750.15  5224.5 1750.16    5396 1752.38  5431.1 1755.36  5447.9 1755.21
  5453.4 1757.12  5470.2 1757.58  5475.8 1759.58  5485.5 1760.08  5492.5 1759.18
  5520.4 1761.16  5810.8 1767.83  5821.2  1768.6  5855.5 1775.33  5865.9 1776.31
  5877.9 1781.47  5910.6  1784.7  5962.4 1787.16  6034.4 1791.28  6050.4 1791.25
#Mann= 4 ,-1 , 0
  4310.8     .05       0    4987     .05       0  4999.4     .05       0
  5962.4     .12       0
Bank Sta=4987,4999.4
XS Rating Curve= 0 ,0
Exp/Cntr=0.3,0.1

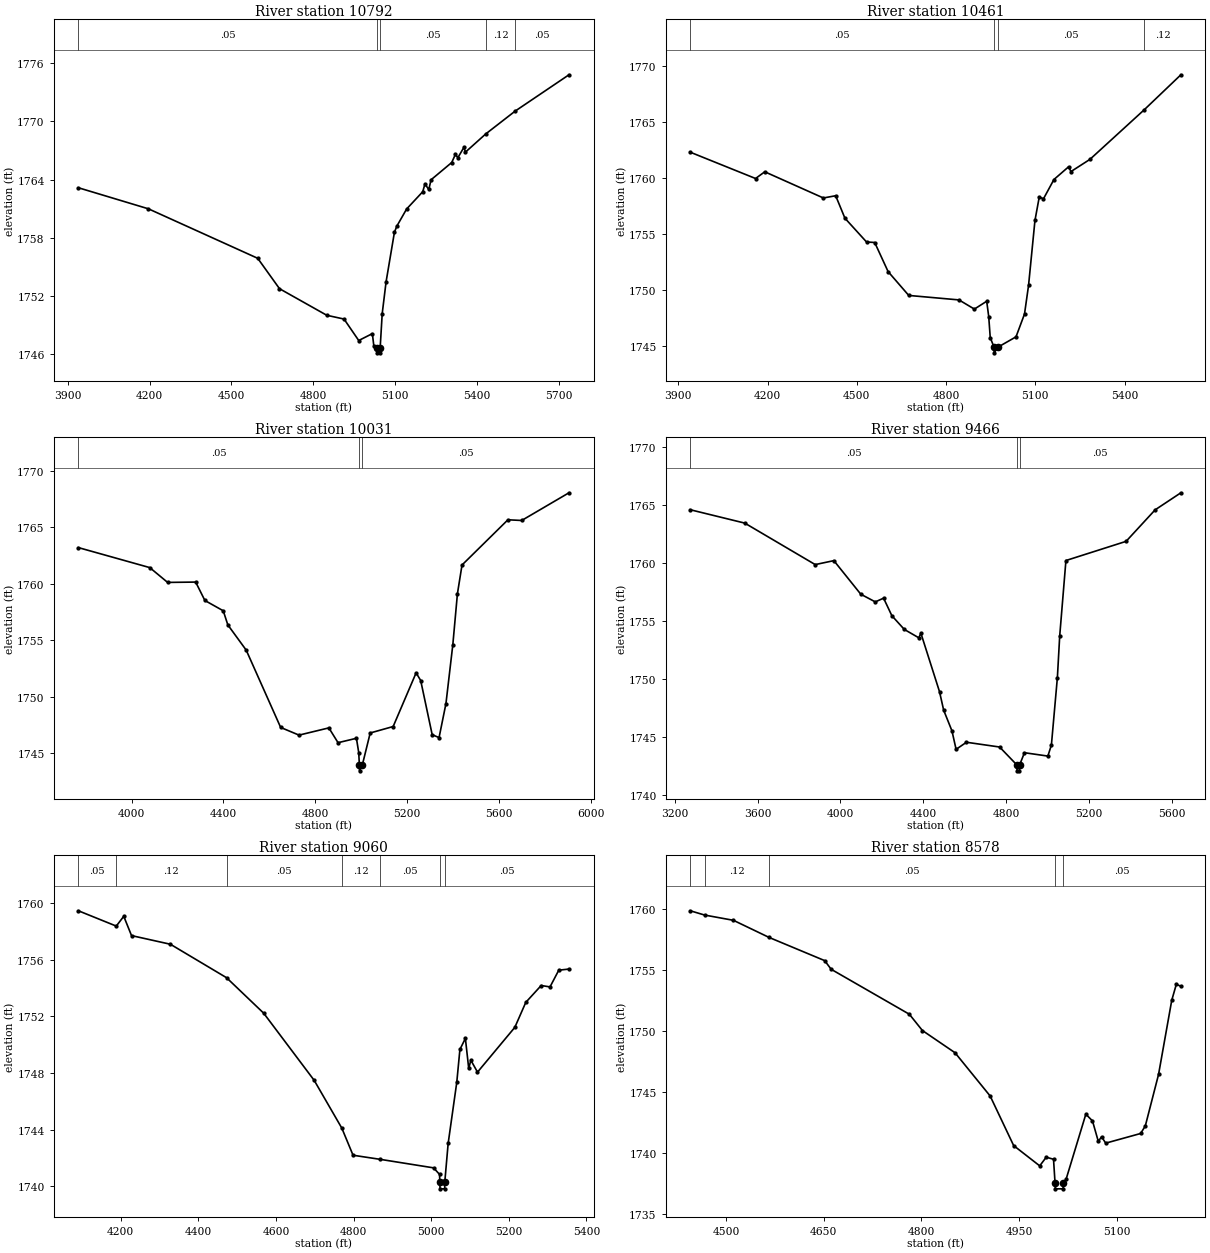
Type RM Length L Ch R = 1 ,10792   ,331,331,331
BEGIN DESCRIPTION:
Elm 02 05 10792.44
END DESCRIPTION:
XS GIS Cut Line= 3
      1597601.67      6825375.62      1598612.09      6825039.68
      1599266.89      6824712.28
#Sta/Elev= 30
  3939.5 1763.15  4195.9 1760.98  4596.4 1755.88  4676.1 1752.75  4849.3 1750.01
  4912.5 1749.62  4966.3 1747.41  5016.2 1748.12  5021.8 1746.81  5032.3 1746.64
  5032.8 1746.14  5044.3 1746.14  5044.8 1746.64  5052.3 1750.18  5066.5 1753.46
    5097 1758.55  5105.6 1759.18  5141.7 1760.96  5200.7 1762.74  5208.8 1763.53
    5223 1762.97  5231.2 1763.97  5306.9 1765.75  5320.6  1766.6  5329.2 1766.24
  5351.6 1767.31  5357.2 1766.82  5431.3 1768.69  5539.4 1771.05  5736.4 1774.79
#Mann= 5 ,-1 , 0
  3939.5     .05       0  5032.3     .05       0  5044.8     .05       0
  5431.3     .12       0  5539.4     .05       0
Bank Sta=5032.3,5044.8
XS Rating Curve= 0 ,0
Exp/Cntr=0.3,0.1

Type RM Length L Ch R = 1 ,10461   ,430,430,430
BEGIN DESCRIPTION:
Elm 02 05 10460.56
END DESCRIPTION:
XS GIS Cut Line= 3
      1597753.25      6825585.25      1598774.07      6825309.21
       1599227.2        6824929.
#Sta/Elev= 30
  3940.1 1762.34  4159.5 1759.99  4190.5 1760.59  4387.4 1758.25  4428.8 1758.45
  4459.9 1756.44  4532.4 1754.32    4560 1754.27    4605 1751.67  4674.4 1749.54
  4843.2 1749.14    4895 1748.32  4936.4 1749.02  4943.2 1747.65  4948.3 1745.77
  4961.2 1744.91  4961.7 1744.41  4973.7 1744.91  5034.9 1745.84  5063.5 1747.88
  5077.1 1750.44  5098.6 1756.24    5113 1758.33  5127.3 1758.18  5162.4  1759.9
  5211.8 1761.04  5219.6 1760.61  5283.4  1761.7  5466.6 1766.15  5589.1 1769.26
#Mann= 4 ,-1 , 0
  3940.1     .05       0  4961.2     .05       0  4973.7     .05       0
  5466.6     .12       0
Bank Sta=4961.2,4973.7
XS Rating Curve= 0 ,0
Exp/Cntr=0.3,0.1

Type RM Length L Ch R = 1 ,10031   ,565,565,565
BEGIN DESCRIPTION:
Elm 02 05 10030.62
END DESCRIPTION:
XS GIS Cut Line= 3
      1597724.11      6825682.91      1598958.44      6825651.66
      1599861.02      6825654.26
#Sta/Elev= 30
  3768.4  1763.2  4079.4 1761.43  4157.2 1760.12  4279.4 1760.15  4319.5 1758.52
  4399.5 1757.61  4419.5 1756.36  4499.5 1754.13  4649.6 1747.29  4729.6 1746.61
  4859.6 1747.25  4899.6 1745.94  4979.7 1746.33  4989.7 1745.07  4992.6 1743.95
  4993.1 1743.45  5005.2 1743.95  5039.7  1746.8  5139.7 1747.37  5239.7 1752.12
  5259.7 1751.44  5309.7 1746.65  5339.7 1746.39  5369.7  1749.4  5399.7 1754.62
  5419.7 1759.12  5439.7 1761.66  5639.7 1765.66  5699.7  1765.6  5905.7 1768.05
#Mann= 3 ,-1 , 0
  3768.4     .05       0  4992.6     .05       0  5005.2     .05       0
Bank Sta=4992.6,5005.2
XS Rating Curve= 0 ,0
Exp/Cntr=0.3,0.1

Type RM Length L Ch R = 1 ,9466    ,406,406,406
BEGIN DESCRIPTION:
Elm 02 05 9465.78
END DESCRIPTION:
XS GIS Cut Line= 3
      1597671.98      6825938.12      1599395.94      6825935.51
      1600039.21      6825904.26
#Sta/Elev= 30
    3275 1764.58    3538 1763.43    3878 1759.86    3968  1760.2    4098 1757.31
    4168 1756.65    4208 1756.97    4248 1755.46    4308 1754.28    4378 1753.56
    4388 1753.96    4478 1748.92    4498 1747.33    4538 1745.55    4558 1743.96
    4608 1744.57    4768 1744.16  4851.7 1742.61  4852.2 1742.11  4863.9 1742.11
  4864.4 1742.61    4888 1743.67    5001 1743.38    5018 1744.33  5046.9 1750.14
  5058.1 1753.72  5088.1 1760.21  5378.5 1761.86  5518.6 1764.57    5643 1766.04
#Mann= 3 ,-1 , 0
    3275     .05       0  4851.7     .05       0  4864.4     .05       0
Bank Sta=4851.7,4864.4
XS Rating Curve= 0 ,0
Exp/Cntr=0.3,0.1

Type RM Length L Ch R = 1 ,9060    ,482,482,482
BEGIN DESCRIPTION:
Elm 02 05 9060.45
END DESCRIPTION:
XS GIS Cut Line= 3
      1598498.24      6826254.96      1599401.02      6826298.36
      1599725.63      6826142.55
#Sta/Elev= 30
    4091 1759.44  4188.6 1758.36  4207.9 1759.05  4227.9 1757.69    4328 1757.08
  4472.7 1754.72  4568.3 1752.22  4698.5 1747.48  4769.7 1744.11  4798.6  1742.2
  4868.6 1741.91    5006 1741.31  5021.4 1740.85  5022.2 1740.33  5022.7 1739.83
  5034.5 1739.83    5035 1740.33  5043.6 1743.03  5065.8 1747.34  5073.9 1749.66
    5088 1750.44  5096.6 1748.32  5102.1  1748.9  5119.2 1748.06  5215.4 1751.22
  5243.6 1752.98  5283.3 1754.17    5306 1754.07  5328.6 1755.25  5354.9 1755.33
#Mann= 7 ,-1 , 0
    4091     .05       0  4188.6     .12       0  4472.7     .05       0
  4769.7     .12       0  4868.6     .05       0  5022.2     .05       0
    5035     .05       0
Bank Sta=5022.2,5035
XS Rating Curve= 0 ,0
Exp/Cntr=0.3,0.1

Type RM Length L Ch R = 1 ,8578    ,410,410,410
BEGIN DESCRIPTION:
Elm 02 05 8578.25
END DESCRIPTION:
XS GIS Cut Line= 3
      1598648.84       6826658.6      1599202.27      6826675.97
      1599398.78      6826642.14
#Sta/Elev= 30
  4445.2 1759.84  4467.2 1759.49  4511.4 1759.06  4566.1 1757.66  4651.5 1755.76
  4661.5 1755.05  4781.5 1751.37  4801.5 1750.04  4851.6 1748.22  4905.5 1744.68
  4941.6 1740.62  4981.6 1738.96  4991.6 1739.67  5002.8  1739.5  5005.1 1737.58
  5005.6 1737.08  5017.5 1737.08    5018 1737.58    5022 1737.85  5052.4 1743.19
  5062.6 1742.64  5071.5 1740.97  5076.6 1741.34  5082.9 1740.82  5136.5 1741.61
  5143.7 1742.23    5164 1746.44  5184.3 1752.52  5191.3 1753.82  5198.3 1753.66
#Mann= 5 ,-1 , 0
  4445.2     .05       0  4467.2     .12       0  4566.1     .05       0
  5005.1     .05       0    5018     .05       0
Bank Sta=5005.1,5018
XS Rating Curve= 0 ,0
Exp/Cntr=0.3,0.1

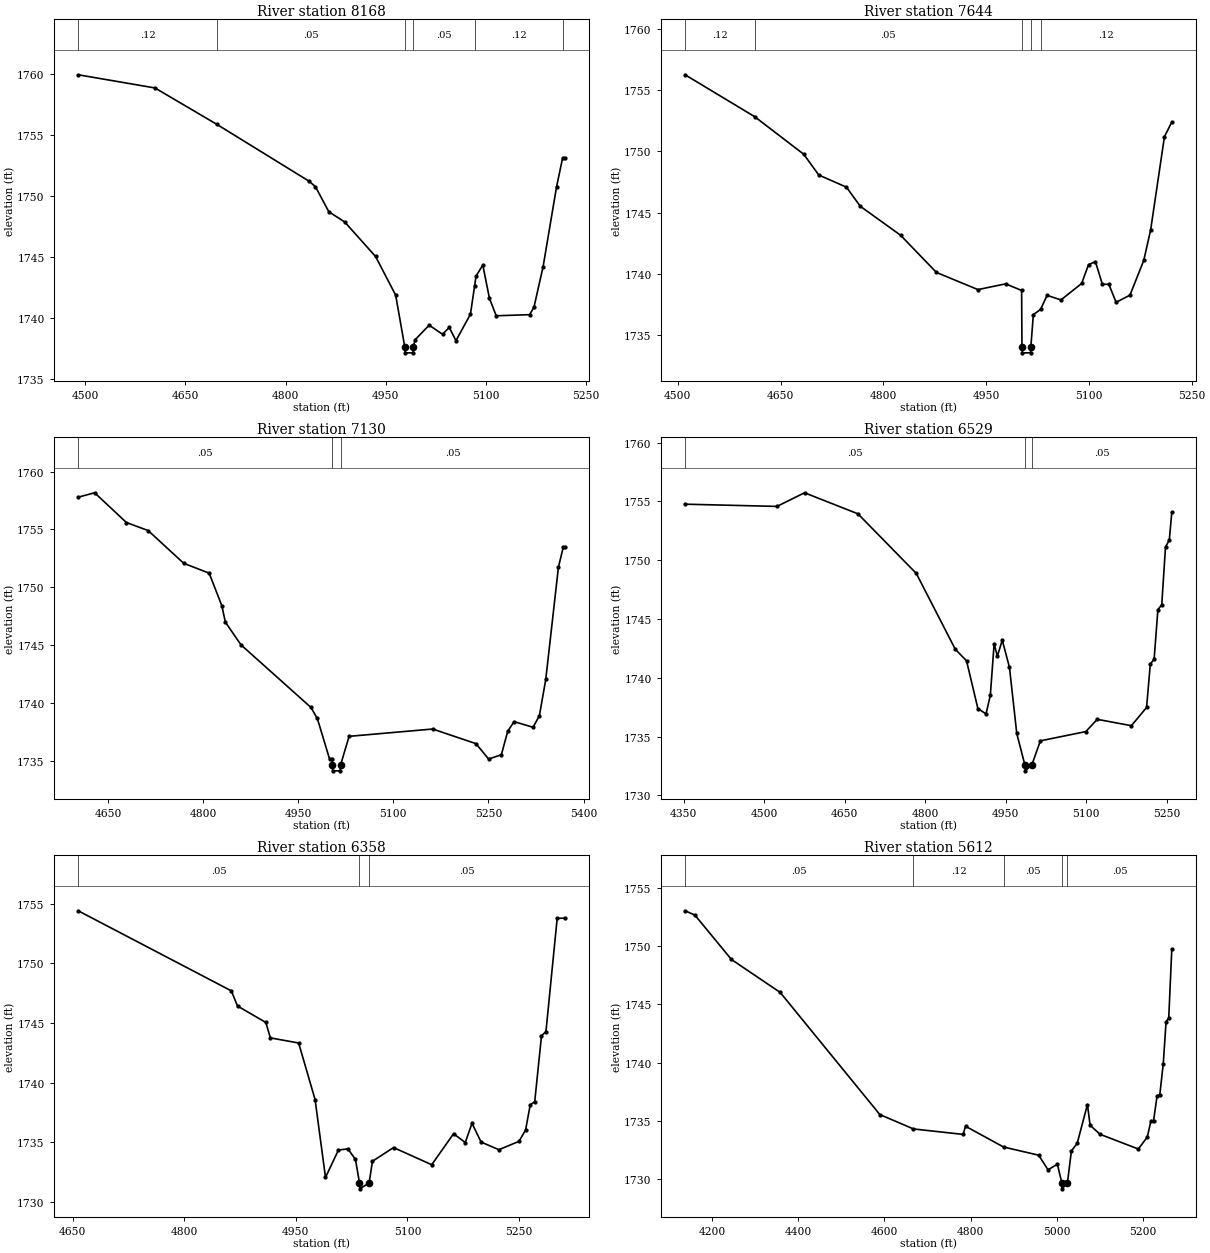
Type RM Length L Ch R = 1 ,8168    ,524,524,524
BEGIN DESCRIPTION:
Elm 02 05 8168.49
END DESCRIPTION:
XS GIS Cut Line= 3
       1598640.2      6827005.83      1599148.02      6827040.55
      1599367.41      6827018.53
#Sta/Elev= 30
  4489.2 1759.96  4604.3 1758.88  4697.2 1755.89  4834.8 1751.25  4844.8 1750.79
  4864.9 1748.73  4888.7 1747.89    4935 1745.06  4965.1 1741.89  4978.7 1737.66
  4979.2 1737.16  4991.1 1737.16  4991.6 1737.66  4994.2 1738.23  5015.3 1739.43
  5035.4 1738.68  5045.4 1739.24  5055.5 1738.16  5077.2 1740.33  5083.5 1742.67
  5085.6 1743.45  5095.7 1744.36  5105.7 1741.62  5115.8  1740.2    5166 1740.29
  5172.5 1740.92  5186.1 1744.22  5206.2 1750.75  5215.4 1753.15  5218.7 1753.15
#Mann= 6 ,-1 , 0
  4489.2     .12       0  4697.2     .05       0  4978.7     .05       0
  4991.6     .05       0  5083.5     .12       0  5215.4     .05       0
Bank Sta=4978.7,4991.6
XS Rating Curve= 0 ,0
Exp/Cntr=0.3,0.1

Type RM Length L Ch R = 1 ,7644    ,514,514,514
BEGIN DESCRIPTION:
Elm 02 05 7643.69
END DESCRIPTION:
XS GIS Cut Line= 3
        1598672.      6827427.91      1599155.97      6827497.36
      1599375.63       6827523.2
#Sta/Elev= 30
  4510.8 1756.25  4612.3 1752.83    4684 1749.76  4705.8 1748.07  4746.2 1747.08
  4766.4 1745.52  4825.1 1743.16  4877.5 1740.12  4938.1 1738.72  4978.5 1739.19
  5001.8 1738.65  5002.3 1734.06  5002.8 1733.56  5014.8 1733.56  5015.3 1734.06
  5018.9 1736.68  5029.4  1737.1    5039 1738.25  5059.2 1737.88  5089.4 1739.22
  5099.4 1740.76  5109.5    1741  5119.6 1739.16  5129.1 1739.15  5139.7 1737.68
  5159.9 1738.27    5180  1741.1  5190.1  1743.6  5210.2  1751.2  5220.9 1752.39
#Mann= 5 ,-1 , 0
  4510.8     .12       0  4612.3     .05       0  5002.3     .05       0
  5015.3     .05       0  5029.4     .12       0
Bank Sta=5002.3,5015.3
XS Rating Curve= 0 ,0
Exp/Cntr=0.3,0.1

Type RM Length L Ch R = 1 ,7130    ,601,601,601
BEGIN DESCRIPTION:
Elm 02 05 7130.05
END DESCRIPTION:
XS GIS Cut Line= 3
      1598609.14      6827864.12       1599008.4      6827896.67
      1599375.12      6827887.99
#Sta/Elev= 30
  4603.1 1757.79    4629 1758.17  4679.2  1755.6  4713.4 1754.91  4769.5 1752.08
  4809.6 1751.23  4829.7 1748.41  4835.1 1747.01  4859.8 1745.04  4970.2 1739.63
  4980.2 1738.68  4999.5 1735.18  5003.7 1735.18  5003.8 1734.66  5004.3 1734.16
  5016.3 1734.16  5016.8 1734.66  5030.3 1737.14    5162 1737.77  5230.3 1736.51
  5250.3 1735.18  5270.4 1735.55  5280.4 1737.57  5290.4 1738.41  5320.4 1737.92
  5330.4 1738.93  5340.4 1742.05  5360.4 1751.75    5368 1753.47  5370.5 1753.47
#Mann= 3 ,-1 , 0
  4603.1     .05       0  5003.8     .05       0  5016.8     .05       0
Bank Sta=5003.8,5016.8
XS Rating Curve= 0 ,0
Exp/Cntr=0.3,0.1

Type RM Length L Ch R = 1 ,6529    ,171,171,171
BEGIN DESCRIPTION:
Elm 02 05 6528.92
END DESCRIPTION:
XS GIS Cut Line= 3
       1598717.4      6828596.75      1599259.06      6828246.06
      1599446.06      6828062.52
#Sta/Elev= 30
  4352.5 1754.76  4523.7 1754.57  4575.1 1755.73  4674.7 1753.94  4783.5 1748.87
  4856.1 1742.43  4877.2 1741.43  4898.3 1737.38  4913.5 1736.92  4921.5  1738.5
  4928.6 1742.89  4934.6 1741.83  4943.8 1743.19  4957.2 1740.88  4970.8 1735.26
  4985.9 1732.58  4986.4 1732.08  4998.9 1732.58  5014.8 1734.63  5099.6 1735.42
  5120.8 1736.46  5184.5 1735.92  5212.8 1737.47  5219.8 1741.17  5226.9 1741.57
  5233.9 1745.79  5241.1 1746.21  5248.1 1751.12  5255.2 1751.71  5259.8 1754.07
#Mann= 3 ,-1 , 0
  4352.5     .05       0  4985.9     .05       0  4998.9     .05       0
Bank Sta=4985.9,4998.9
XS Rating Curve= 0 ,0
Exp/Cntr=0.3,0.1

Type RM Length L Ch R = 1 ,6358    ,746,746,746
BEGIN DESCRIPTION:
Mapping XS 9590943f
END DESCRIPTION:
XS GIS Cut Line= 4
       1599215.5      6828626.35      1599347.43      6828438.88
      1599465.49      6828185.41      1599545.36      6828063.86
#Sta/Elev= 30
  4657.4  1754.4  4863.3 1747.69  4871.6 1746.42  4909.7 1745.04  4915.8 1743.75
  4953.8 1743.32  4975.9 1738.58  4989.9 1732.06  5007.3 1734.35    5020 1734.45
  5030.2 1733.56  5035.6  1731.6  5036.1  1731.1  5048.6  1731.6    5053 1733.41
  5081.4 1734.56  5132.7 1733.12  5162.1 1735.72  5177.8 1734.98  5186.9 1736.59
  5199.1 1735.02    5223 1734.38  5250.1 1735.08  5258.9 1736.03  5265.2 1738.15
  5271.2  1738.4  5280.3 1743.92  5286.3 1744.28  5301.4 1753.77  5311.7 1753.78
#Mann= 3 ,-1 , 0
  4657.4     .05       0  5035.6     .05       0  5048.6     .05       0
Bank Sta=5035.6,5048.6
XS Rating Curve= 0 ,0
Exp/Cntr=0.3,0.1

Type RM Length L Ch R = 1 ,5612    ,1140,1140,1140
BEGIN DESCRIPTION:
Mapping XS 52700ffa
END DESCRIPTION:
XS GIS Cut Line= 4
      1599267.55      6828681.95      1599562.71      6828435.41
      1600125.21       6828199.3      1600208.02      6828092.33
#Sta/Elev= 30
  4137.1 1753.01  4159.8 1752.64  4244.6 1748.84  4357.8 1746.02  4589.2 1735.56
  4667.2 1734.33  4782.6 1733.86  4788.1 1734.56  4876.6 1732.78    4958 1732.08
  4979.7 1730.83  5001.4 1731.31  5011.7  1729.7  5012.2  1729.2  5024.7  1729.7
  5033.9 1732.44  5047.4  1733.1  5071.2 1736.42  5077.3 1734.65  5100.4 1733.87
  5189.4 1732.61  5210.2 1733.64  5218.4 1734.99  5224.7 1735.04  5232.9 1737.16
  5239.2 1737.26  5247.2  1739.9  5253.7 1743.48    5260 1743.86    5267  1749.7
#Mann= 5 ,-1 , 0
  4137.1     .05       0  4667.2     .12       0  4876.6     .05       0
  5011.7     .05       0  5024.7     .05       0
Bank Sta=5011.7,5024.7
XS Rating Curve= 0 ,0
Exp/Cntr=0.3,0.1

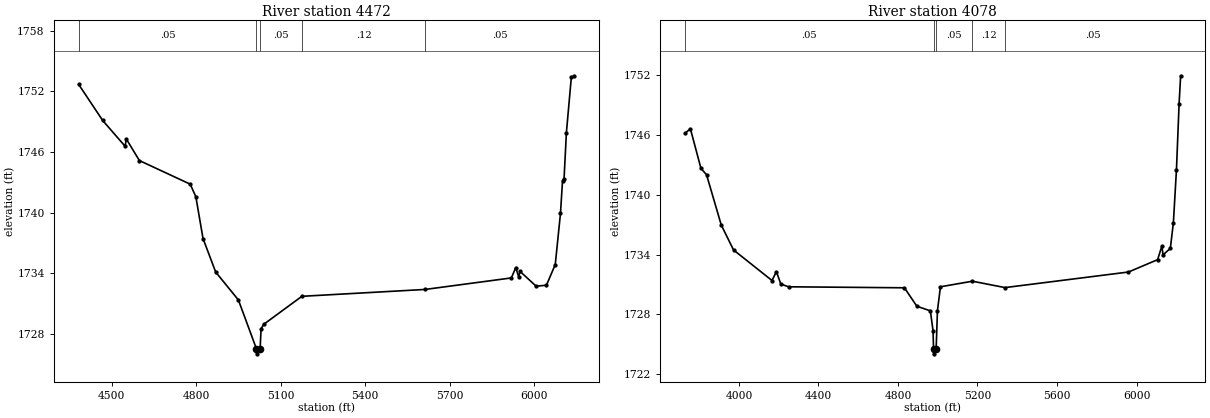
Type RM Length L Ch R = 1 ,4472    ,394,394,394
BEGIN DESCRIPTION:
Mapping XS 6ecbb148
END DESCRIPTION:
XS GIS Cut Line= 5
      1599239.75      6828956.25      1599680.76      6828921.52
      1600059.24      6828872.91      1600312.71      6828584.72
      1600492.81      6828061.72
#Sta/Elev= 30
  4381.9  1752.7  4467.4 1749.12  4546.6 1746.58  4551.7 1747.27  4597.8 1745.15
  4778.4 1742.81  4798.4 1741.56  4823.9 1737.42  4868.9  1734.1  4949.5 1731.34
  5013.6  1726.5  5014.1    1726  5026.7  1726.5  5030.2 1728.49  5040.3 1728.94
  5175.1  1731.7  5612.9 1732.38  5919.3 1733.52  5935.2 1734.55  5945.2 1733.64
  5950.5 1734.16  6007.6  1732.7  6044.1  1732.8  6075.4 1734.85  6093.9 1739.91
  6101.3 1743.17  6106.6 1743.33    6115 1747.93  6132.5 1753.41  6142.8 1753.55
#Mann= 5 ,-1 , 0
  4381.9     .05       0  5013.6     .05       0  5026.7     .05       0
  5175.1     .12       0  5612.9     .05       0
Bank Sta=5013.6,5026.7
XS Rating Curve= 0 ,0
Exp/Cntr=0.3,0.1

Type RM Length L Ch R = 1 ,4078    ,0,0,0
BEGIN DESCRIPTION:
Elm 02 05 5780.924
END DESCRIPTION:
XS GIS Cut Line= 3
      1598930.77      6829609.02      1600322.44      6828939.86
       1600818.7      6828131.41
#Sta/Elev= 30
    3729 1746.16  3755.9 1746.61    3809 1742.64  3837.2    1742  3911.2 1736.96
    3973 1734.46  4166.4  1731.4  4188.6 1732.29  4210.8 1731.04  4250.1 1730.77
  4832.6 1730.67    4895 1728.82  4962.9 1728.36  4976.4 1726.38    4979 1724.55
  4979.5 1724.05  4992.1 1724.55  4998.6 1728.38  5013.7 1730.77  5174.4 1731.33
  5338.4 1730.69  5959.2 1732.25  6106.1 1733.49  6127.4 1734.86  6133.3 1733.97
    6170 1734.62  6185.4 1737.21  6200.8 1742.51  6214.1 1749.13  6221.8 1751.92
#Mann= 5 ,-1 , 0
    3729     .05       0    4979     .05       0  4992.1     .05       0
  5174.4     .12       0  5338.4     .05       0
Bank Sta=4979,4992.1
XS Rating Curve= 0 ,0
Exp/Cntr=0.3,0.1

Chan Stop Cuts=-1
Use User Specified Reach Order=0
Composite Channel Slope=5