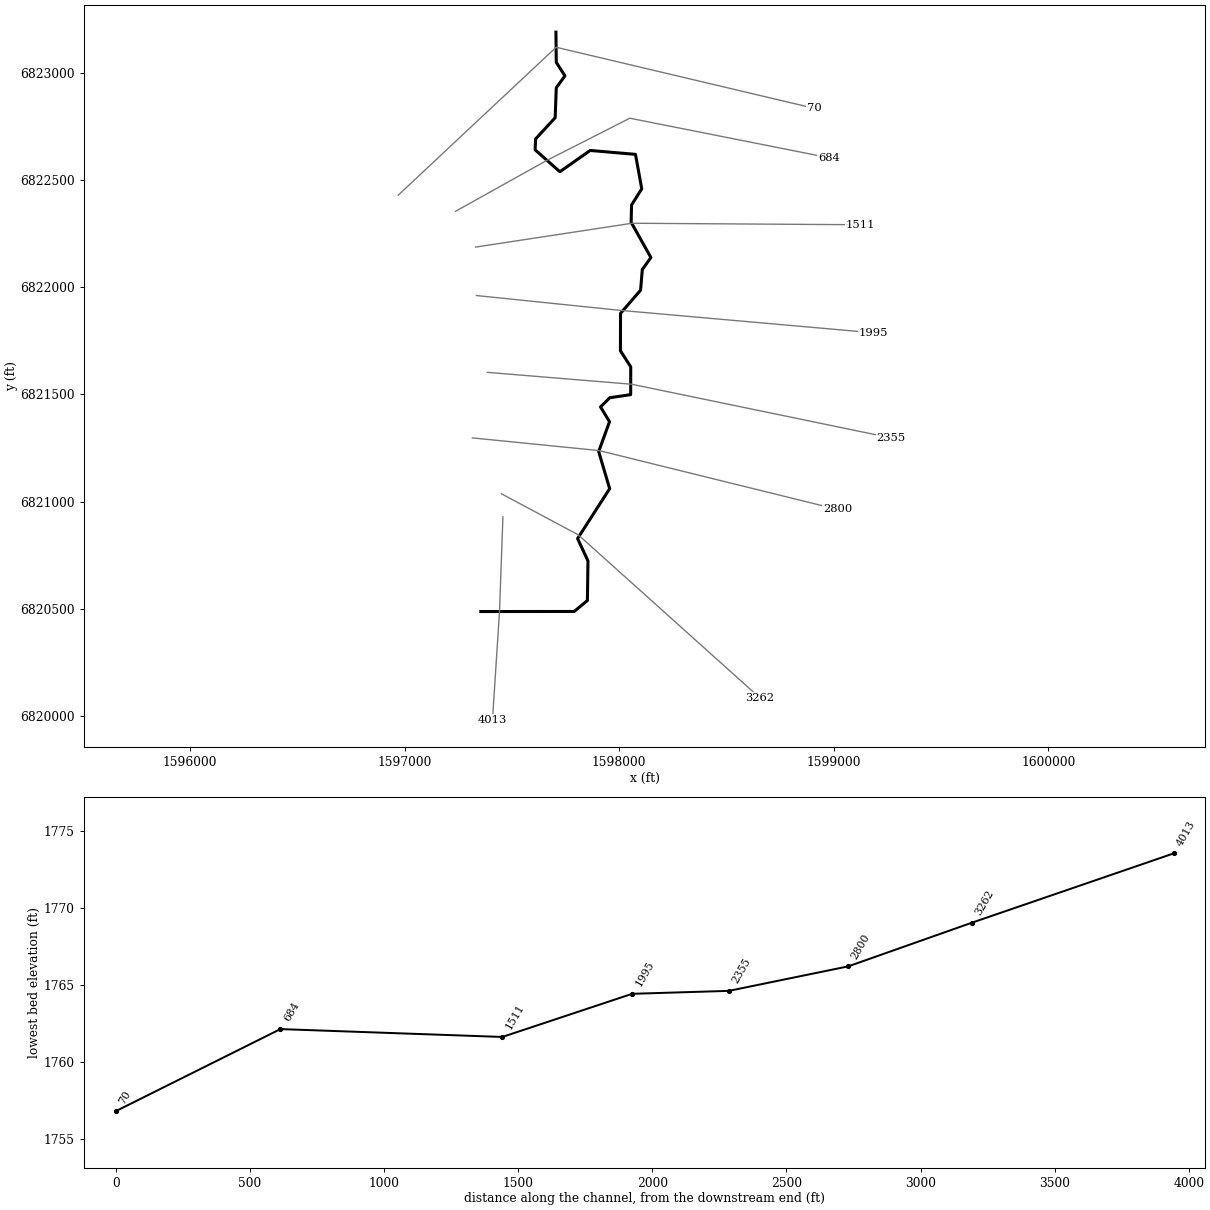
--- Elm 02 06.prj (project) ---

Proj Title=Elm 02 06 Base Level Engineering
Current Plan=p01
Default Exp/Contr=0.3,0.1
English Units
Geom File=g01
Flow File=f01
Plan File=p01
BEGIN DESCRIPTION:
Elm 02 06
END DESCRIPTION:

--- Elm 02 06.p01 (plan) ---

Plan Title=Multiple Run
Short Identifier=Multiple
Geom File=g01
Flow File=f01
Subcritical Flow
K Sum by GR= 0
Std Step Tol= 0.01
Critical Tol= 0.01
Num of Std Step Trials= 20
Max Error Tol= 0.3
Flow Tol Ratio= 0.001
Split Flow NTrial= 30
Split Flow Tol= 0.02
Split Flow Ratio= 0.02
Log Output Level= 0
Friction Slope Method= 1
Unsteady Friction Slope Method= 2
Unsteady Bridges Friction Slope Method= 1
Parabolic Critical Depth
Global Vel Dist=  1 , 1 , 1
Global Log Level= 0
CheckData=True
Encroach Param= -1, 0, 0, 0
BEGIN DESCRIPTION:
Multiple Run
END DESCRIPTION:

--- Elm 02 06.f01 (steady flow) ---

Flow Title=Multiple
Number of Profiles=7
Profile Names=10-year,25-year,50-year,1pct_min,100-year,1pct_plu,500-year
River Rch & RM= Elm 02 06,Reach-1,4013
     178     240     290     217     348     479     508
River Rch & RM= Elm 02 06,Reach-1,2800
     286     397     489     373     598     823     906
Boundary for River Rch & Prof#=Elm 02 06,Reach-1,1
Up Type=0
Dn Type=3
Dn Slope=0.001
Boundary for River Rch & Prof#=Elm 02 06,Reach-1,2
Up Type=0
Dn Type=3
Dn Slope=0.001
Boundary for River Rch & Prof#=Elm 02 06,Reach-1,3
Up Type=0
Dn Type=3
Dn Slope=0.001
Boundary for River Rch & Prof#=Elm 02 06,Reach-1,4
Up Type=0
Dn Type=3
Dn Slope=0.001
Boundary for River Rch & Prof#=Elm 02 06,Reach-1,5
Up Type=0
Dn Type=3
Dn Slope=0.001
Boundary for River Rch & Prof#=Elm 02 06,Reach-1,6
Up Type=0
Dn Type=3
Dn Slope=0.001
Boundary for River Rch & Prof#=Elm 02 06,Reach-1,7
Up Type=0
Dn Type=3
Dn Slope=0.001

--- Elm 02 06.g01 (geometry) ---

Geom Title=Existing Conditions

River Reach=Elm 02 06,Reach-1
Reach XY= 30
      1597355.00      6820488.00      1597789.98      6820488.32
      1597851.57      6820539.22      1597854.30      6820724.09
      1597805.91      6820828.16      1597955.38      6821060.72
      1597904.19      6821233.43      1597954.76      6821372.67
      1597912.71      6821441.69      1597956.10      6821484.36
      1598053.29      6821498.85      1598053.64      6821628.32
      1598005.52      6821703.22      1598006.05      6821877.56
      1598099.46      6821985.58      1598107.56      6822082.10
      1598147.47      6822138.01      1598055.54      6822301.97
      1598057.29      6822382.43      1598104.95      6822458.04
      1598075.66      6822618.60      1597864.59      6822636.79
      1597723.40      6822537.63      1597608.09      6822639.63
      1597610.08      6822690.28      1597701.44      6822789.47
      1597706.56      6822928.40      1597746.92      6822984.70
      1597706.51      6823047.57      1597705.00      6823188.00

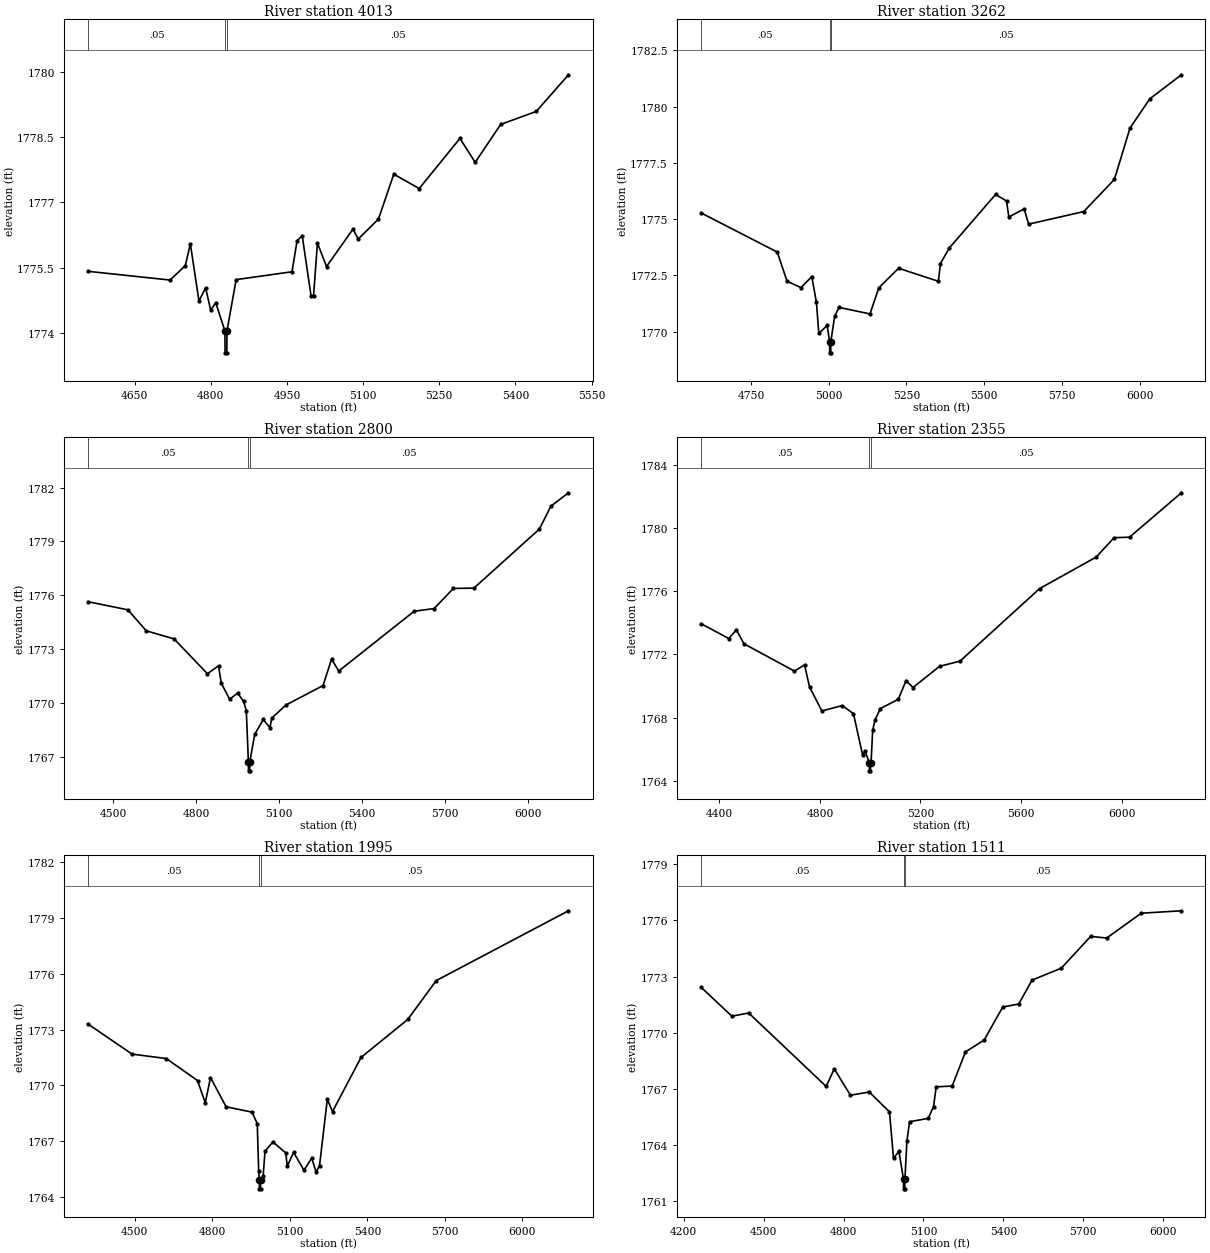
Type RM Length L Ch R = 1,4013,751,751,751
BEGIN DESCRIPTION:
Elm 02 06 1035.142
END DESCRIPTION:
XS GIS Cut Line= 3
      1597457.96      6820929.18      1597442.00      6820488.06
      1597409.35      6819984.72
#Sta/Elev= 30
  4558.6 1775.42  4719.9 1775.22  4749.9 1775.55  4759.9 1776.05  4776.8 1774.74
  4789.9 1775.04  4799.9 1774.53  4809.9 1774.70  4828.0 1774.05  4828.2 1773.55
  4831.7 1773.55  4832.0 1774.05  4850.0 1775.23  4960.0 1775.41  4970.0 1776.12
  4980.1 1776.24  4997.5 1774.86  5002.5 1774.86  5010.1 1776.07  5028.0 1775.53
  5080.2 1776.39  5090.3 1776.16  5130.3 1776.62  5160.4 1777.65  5210.5 1777.32
  5290.7 1778.47  5320.7 1777.92  5370.8 1778.79  5441.0 1779.09  5504.4 1779.93
#Mann=3,-1,0
  4558.6    0.05       0  4828.0    0.05       0  4832.0    0.05       0
Bank Sta=4828,4832
Exp/Cntr=0.3,0.1

Type RM Length L Ch R = 1,3262,462,462,462
BEGIN DESCRIPTION:
Elm 02 06 3261.81
END DESCRIPTION:
XS GIS Cut Line= 3
      1597451.00      6821036.78      1597808.65      6820845.80
      1598655.90      6820085.36
#Sta/Elev= 30
  4589.8 1775.28  4834.7 1773.54  4866.4 1772.24  4911.2 1771.96  4945.8 1772.45
  4960.7 1771.30  4968.4 1769.92  4995.2 1770.28  5003.0 1769.56  5003.2 1769.06
  5006.7 1769.06  5007.0 1769.56  5019.2 1770.68  5033.4 1771.08  5132.8 1770.79
  5161.2 1771.95  5224.7 1772.82  5352.6 1772.24  5359.3 1773.03  5387.7 1773.72
  5536.5 1776.10  5571.6 1775.81  5579.1 1775.10  5628.4 1775.46  5642.6 1774.78
  5819.8 1775.34  5918.4 1776.77  5968.5 1779.05  6032.1 1780.35  6133.7 1781.42
#Mann=3,-1,0
  4589.8    0.05       0  5003.0    0.05       0  5007.0    0.05       0
Bank Sta=5003,5007
Exp/Cntr=0.3,0.1

Type RM Length L Ch R = 1,2800,445,445,445
BEGIN DESCRIPTION:
Elm 02 06 2799.81
END DESCRIPTION:
XS GIS Cut Line= 3
      1597315.63      6821297.19      1597905.87      6821238.16
      1599017.03      6820963.85
#Sta/Elev= 30
  4408.4 1775.64  4552.2 1775.19  4618.8 1774.02  4719.3 1773.57  4839.9 1771.63
  4880.1 1772.07  4890.2 1771.10  4920.3 1770.21  4949.2 1770.55  4970.6 1770.09
  4980.6 1769.58  4988.2 1766.72  4988.6 1766.22  4992.8 1766.22  4993.2 1766.72
  5011.0 1768.25  5041.9 1769.08  5066.2 1768.62  5072.8 1769.16  5124.3 1769.89
  5258.2 1770.97  5289.1 1772.44  5315.0 1771.78  5587.8 1775.11  5659.9 1775.26
  5729.6 1776.38  5804.1 1776.40  6041.0 1779.69  6082.2 1780.96  6146.1 1781.71
#Mann=3,-1,0
  4408.4    0.05       0  4988.2    0.05       0  4993.2    0.05       0
Bank Sta=4988.2,4993.2
Exp/Cntr=0.3,0.1

Type RM Length L Ch R = 1,2355,360,360,360
BEGIN DESCRIPTION:
Elm 02 06 2355.05
END DESCRIPTION:
XS GIS Cut Line= 3
      1597385.04      6821602.75      1598058.65      6821547.19
      1599266.96      6821297.19
#Sta/Elev= 30
  4327.5 1773.94  4437.8 1773.00  4467.9 1773.55  4498.0 1772.67  4698.7 1770.94
  4738.9 1771.33  4758.9 1769.94  4807.6 1768.42  4889.4 1768.76  4933.6 1768.24
  4969.6 1765.65  4979.7 1765.89  4996.6 1765.13  4997.0 1764.63  5001.2 1764.63
  5001.6 1765.13  5003.4 1765.13  5009.9 1767.19  5019.5 1767.86  5040.5 1768.57
  5112.0 1769.16  5142.6 1770.34  5170.2 1769.90  5275.7 1771.24  5357.1 1771.57
  5673.7 1776.16  5898.3 1778.15  5969.8 1779.38  6031.1 1779.41  6237.3 1782.22
#Mann=3,-1,0
  4327.5    0.05       0  4996.6    0.05       0  5001.6    0.05       0
Bank Sta=4996.6,5001.6
Exp/Cntr=0.3,0.1

Type RM Length L Ch R = 1,1995,484,484,484
BEGIN DESCRIPTION:
Elm 02 06 1994.99
END DESCRIPTION:
XS GIS Cut Line= 3
      1597333.96      6821960.74      1598007.61      6821891.29
      1599184.69      6821787.12
#Sta/Elev= 30
  4319.5 1773.29  4489.4 1771.68  4622.1 1771.44  4742.8 1770.26  4772.9 1769.06
  4793.0 1770.42  4853.4 1768.85  4953.9 1768.56  4974.0 1767.94  4979.5 1765.39
  4982.0 1764.94  4982.4 1764.44  4986.7 1764.44  4987.0 1764.94  4996.7 1765.13
  5004.1 1766.46  5034.3 1766.96  5084.5 1766.37  5090.1 1765.65  5114.6 1766.40
  5154.7 1765.44  5184.8 1766.09  5202.0 1765.34  5215.0 1765.69  5245.1 1769.25
  5265.2 1768.59  5375.6 1771.50  5556.3 1773.54  5666.7 1775.63  6178.4 1779.38
#Mann=3,-1,0
  4319.5    0.05       0  4982.0    0.05       0  4987.0    0.05       0
Bank Sta=4982,4987
Exp/Cntr=0.3,0.1

Type RM Length L Ch R = 1,1511,827,827,827
BEGIN DESCRIPTION:
Elm 02 06 1511.16
END DESCRIPTION:
XS GIS Cut Line= 3
      1597330.52      6822186.43      1598059.69      6822297.54
      1599125.68      6822290.59
#Sta/Elev= 30
  4264.8 1772.43  4380.6 1770.88  4443.8 1771.05  4734.6 1767.12  4765.0 1768.06
  4825.7 1766.65  4896.5 1766.82  4972.3 1765.76  4987.5 1763.27  5007.7 1763.65
  5025.1 1762.14  5025.5 1761.64  5029.9 1761.64  5030.3 1762.14  5037.7 1764.18
  5047.7 1765.23  5117.7 1765.41  5137.7 1766.04  5147.7 1767.10  5207.7 1767.14
  5257.7 1768.97  5327.7 1769.60  5397.7 1771.37  5457.7 1771.53  5507.7 1772.81
  5617.7 1773.45  5727.7 1775.15  5787.7 1775.06  5917.7 1776.39  6068.4 1776.52
#Mann=3,-1,0
  4264.8    0.05       0  5025.1    0.05       0  5030.3    0.05       0
Bank Sta=5025.1,5030.3
Exp/Cntr=0.3,0.1

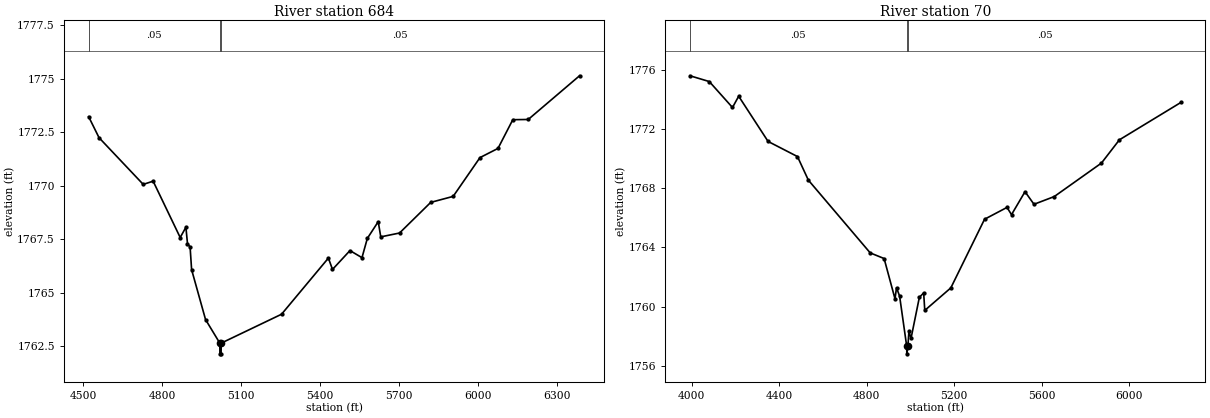
Type RM Length L Ch R = 1,684,614,614,614
BEGIN DESCRIPTION:
Elm 02 06 683.88
END DESCRIPTION:
XS GIS Cut Line= 4
      1597236.76      6822353.09      1597660.39      6822589.20
      1598049.28      6822787.12      1598976.35      6822603.09
#Sta/Elev= 30
  4520.2 1773.22  4559.7 1772.24  4727.7 1770.06  4765.4 1770.21  4868.3 1767.58
  4890.0 1768.06  4896.0 1767.30  4906.0 1767.13  4911.7 1766.08  4964.7 1763.75
  5018.9 1762.65  5019.3 1762.15  5023.8 1762.15  5024.2 1762.65  5253.8 1764.00
  5431.8 1766.62  5447.4 1766.09  5513.8 1766.97  5559.5 1766.64  5579.9 1767.54
  5621.3 1768.32  5630.9 1767.61  5702.3 1767.79  5820.9 1769.22  5906.2 1769.50
  6008.1 1771.31  6076.7 1771.74  6133.0 1773.08  6191.6 1773.09  6386.7 1775.13
#Mann=3,-1,0
  4520.2    0.05       0  5018.9    0.05       0  5024.2    0.05       0
Bank Sta=5018.9,5024.2
Exp/Cntr=0.3,0.1

Type RM Length L Ch R = 1,70,0,0,0
BEGIN DESCRIPTION:
Elm 02 06 560.833
END DESCRIPTION:
XS GIS Cut Line= 3
      1596970.07      6822428.41      1597705.75      6823117.78
      1598908.36      6822833.30
#Sta/Elev= 30
  3991.8 1775.58  4080.1 1775.19  4186.1 1773.44  4214.4 1774.20  4348.8 1771.15
  4483.1 1770.13  4532.9 1768.54  4815.7 1763.63  4879.2 1763.25  4929.0 1760.53
  4935.9 1761.28  4950.1 1760.71  4982.6 1757.32  4983.0 1756.82  4987.9 1757.32
  4992.6 1758.33  5002.2 1757.86  5040.3 1760.63  5060.0 1760.93  5065.1 1759.75
  5184.2 1761.27  5338.3 1765.90  5441.1 1766.70  5461.6 1766.21  5523.3 1767.76
  5564.4 1766.91  5656.9 1767.43  5872.7 1769.69  5954.9 1771.26  6235.8 1773.78
#Mann=3,-1,0
  3991.8    0.05       0  4982.6    0.05       0  4987.9    0.05       0
Bank Sta=4982.6,4987.9
Exp/Cntr=0.3,0.1

Chan Stop Cuts=-1