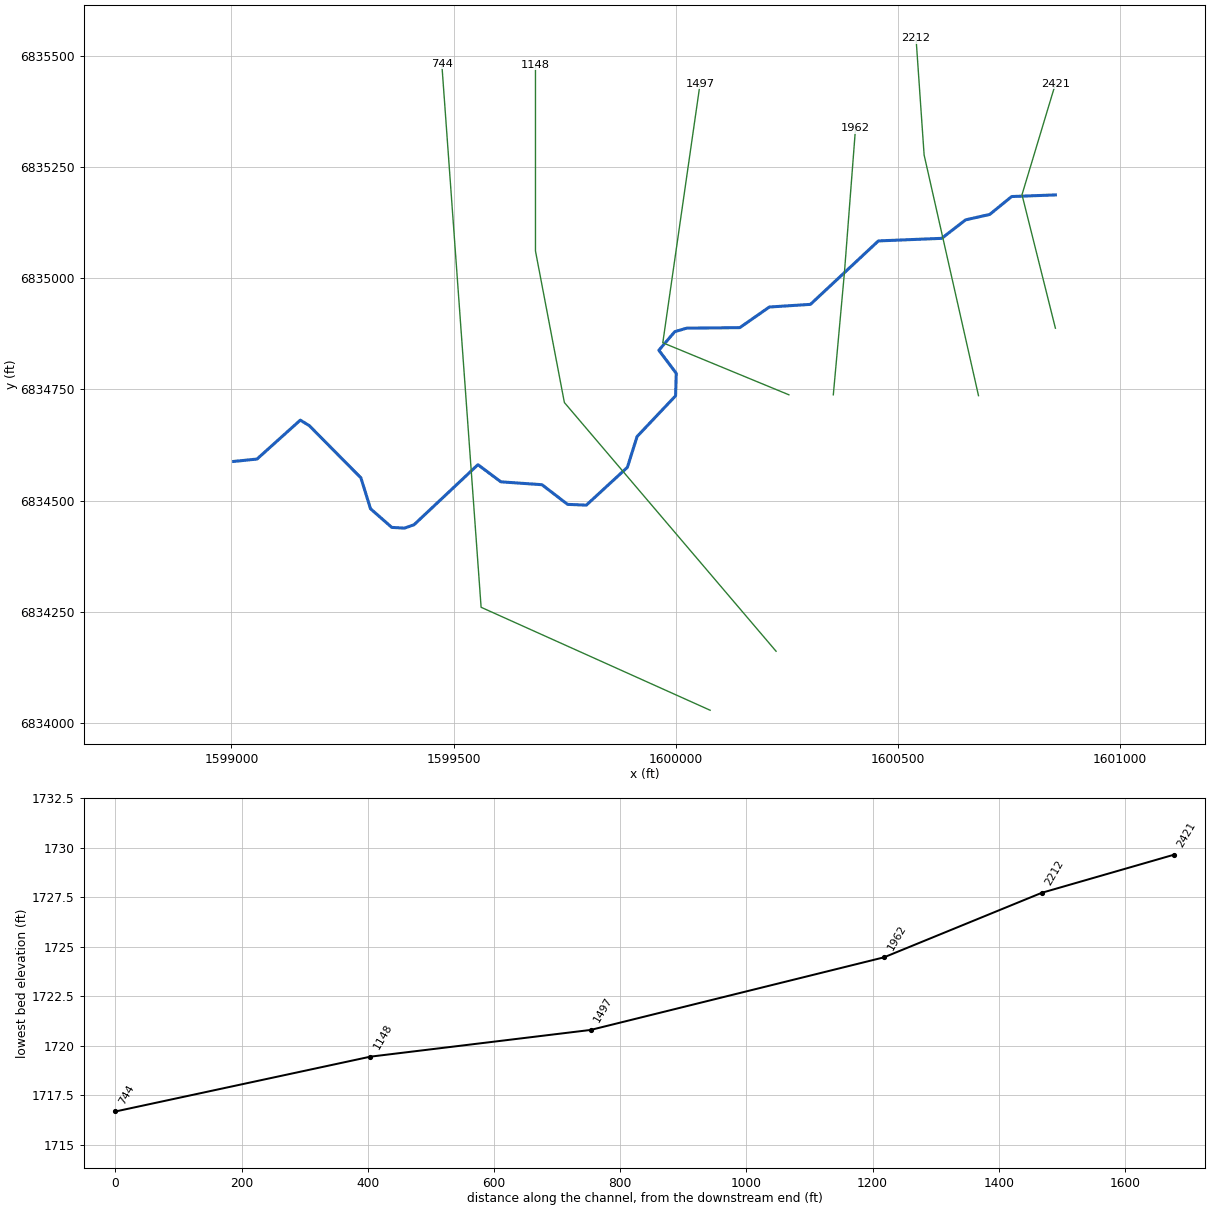
--- Elm 02 07.prj (project) ---

Proj Title=Elm 02 07 Base Level Engineering
Current Plan=p01
Default Exp/Contr=0.3,0.1
English Units
Geom File=g01
Flow File=f01
Plan File=p01
BEGIN DESCRIPTION:
Elm 02 07
END DESCRIPTION:

--- Elm 02 07.p01 (plan) ---

Plan Title=Multiple Run
Short Identifier=Multiple
Geom File=g01
Flow File=f01
Subcritical Flow
K Sum by GR= 0
Std Step Tol= 0.01
Critical Tol= 0.01
Num of Std Step Trials= 20
Max Error Tol= 0.3
Flow Tol Ratio= 0.001
Split Flow NTrial= 30
Split Flow Tol= 0.02
Split Flow Ratio= 0.02
Log Output Level= 0
Friction Slope Method= 1
Unsteady Friction Slope Method= 2
Unsteady Bridges Friction Slope Method= 1
Parabolic Critical Depth
Global Vel Dist=  1 , 1 , 1
Global Log Level= 0
CheckData=True
Encroach Param= -1, 0, 0, 0
BEGIN DESCRIPTION:
Multiple Run
END DESCRIPTION:

--- Elm 02 07.f01 (steady flow) ---

Flow Title=Multiple
Number of Profiles=7
Profile Names=10-year,25-year,50-year,1pct_min,100-year,1pct_plu,500-year
River Rch & RM= Elm 02 07,Reach-1,2421
     107     142     170     126     202     278     290
Boundary for River Rch & Prof#=Elm 02 07,Reach-1,1
Up Type=0
Dn Type=3
Dn Slope=0.001
Boundary for River Rch & Prof#=Elm 02 07,Reach-1,2
Up Type=0
Dn Type=3
Dn Slope=0.001
Boundary for River Rch & Prof#=Elm 02 07,Reach-1,3
Up Type=0
Dn Type=3
Dn Slope=0.001
Boundary for River Rch & Prof#=Elm 02 07,Reach-1,4
Up Type=0
Dn Type=3
Dn Slope=0.001
Boundary for River Rch & Prof#=Elm 02 07,Reach-1,5
Up Type=0
Dn Type=3
Dn Slope=0.001
Boundary for River Rch & Prof#=Elm 02 07,Reach-1,6
Up Type=0
Dn Type=3
Dn Slope=0.001
Boundary for River Rch & Prof#=Elm 02 07,Reach-1,7
Up Type=0
Dn Type=3
Dn Slope=0.001

--- Elm 02 07.g01 (geometry) ---

Geom Title=Existing Conditions

River Reach=Elm 02 07,Reach-1
Reach XY= 30
      1600855.00      6835188.00      1600756.50      6835184.37
      1600707.19      6835144.09      1600652.82      6835131.88
      1600599.07      6835090.25      1600456.47      6835084.46
      1600303.50      6834941.61      1600210.98      6834935.64
      1600144.49      6834889.23      1600024.76      6834888.02
      1599998.17      6834880.19      1599962.25      6834838.33
      1600001.41      6834786.37      1599999.87      6834735.72
      1599913.18      6834644.04      1599891.38      6834574.76
      1599798.98      6834489.61      1599756.75      6834491.34
      1599699.03      6834535.62      1599606.50      6834542.10
      1599554.90      6834580.69      1599411.03      6834445.45
      1599389.58      6834437.87      1599360.87      6834439.50
      1599313.04      6834481.57      1599291.36      6834551.20
      1599175.00      6834668.79      1599155.00      6834680.94
      1599057.52      6834593.35      1599005.00      6834588.00

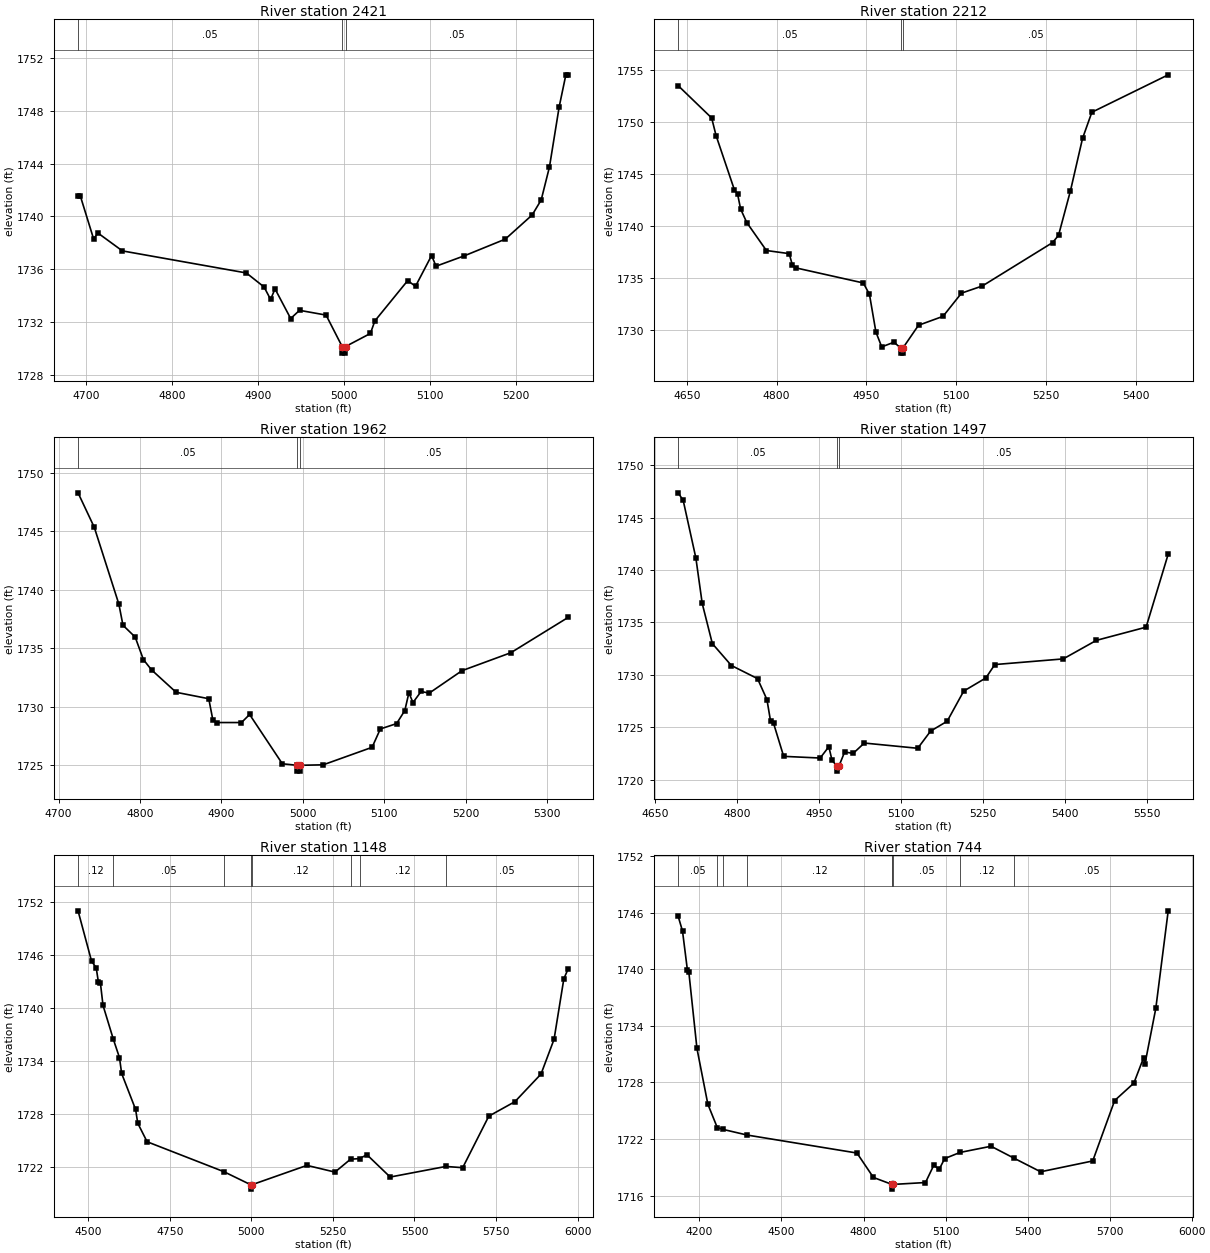
Type RM Length L Ch R = 1,2421,209,209,209
BEGIN DESCRIPTION:
Elm 02 07 2421.01
END DESCRIPTION:
XS GIS Cut Line= 3
      1600855.01      6834887.95      1600779.80      6835188.48
      1600855.00      6835438.00
#Sta/Elev= 30
  4690.2 1741.56  4692.8 1741.56  4708.3 1738.30  4713.4 1738.74  4741.8 1737.39
  4886.1 1735.72  4906.7 1734.66  4914.3 1733.72  4919.5 1734.51  4937.7 1732.27
  4948.0 1732.89  4978.9 1732.53  4997.6 1730.15  4997.8 1729.65  5001.3 1729.65
  5001.6 1730.15  5030.5 1731.14  5035.7 1732.09  5073.9 1735.14  5083.0 1734.71
  5101.7 1737.04  5106.9 1736.23  5139.9 1737.02  5187.5 1738.28  5218.8 1740.11
  5229.3 1741.25  5238.9 1743.74  5250.2 1748.29  5258.0 1750.72  5260.6 1750.72
#Mann=3,-1,0
  4690.2    0.05       0  4997.6    0.05       0  5001.6    0.05       0
Bank Sta=4997.6,5001.6
Exp/Cntr=0.3,0.1

Type RM Length L Ch R = 1,2212,250,250,250
BEGIN DESCRIPTION:
Mapping XS 45996de4
END DESCRIPTION:
XS GIS Cut Line= 3
      1600681.85      6834736.16      1600559.45      6835277.86
      1600541.22      6835540.87
#Sta/Elev= 30
  4635.6 1753.46  4691.6 1750.35  4699.0 1748.65  4729.7 1743.42  4734.8 1743.06
  4740.0 1741.59  4750.3 1740.29  4783.1 1737.60  4821.2 1737.30  4826.3 1736.24
  4832.3 1735.93  4945.0 1734.48  4955.3 1733.39  4966.1 1729.76  4975.8 1728.33
  4996.3 1728.78  5007.3 1728.23  5007.6 1727.73  5011.1 1727.73  5011.3 1728.23
  5037.3 1730.41  5078.3 1731.27  5109.1 1733.50  5144.0 1734.19  5261.3 1738.36
  5271.3 1739.06  5291.3 1743.36  5311.4 1748.38  5327.0 1750.90  5454.6 1754.50
#Mann=3,-1,0
  4635.6    0.05       0  5007.3    0.05       0  5011.3    0.05       0
Bank Sta=5007.3,5011.3
Exp/Cntr=0.3,0.1

Type RM Length L Ch R = 1,1962,465,465,465
BEGIN DESCRIPTION:
Elm 02 07 1961.733
END DESCRIPTION:
XS GIS Cut Line= 3
      1600355.00      6834738.04      1600380.00      6835013.01
      1600405.00      6835338.05
#Sta/Elev= 30
  4723.9 1748.30  4743.9 1745.34  4774.1 1738.76  4779.1 1736.96  4794.1 1735.95
  4804.2 1734.02  4814.2 1733.14  4844.4 1731.22  4884.5 1730.67  4889.6 1728.83
  4894.6 1728.63  4924.7 1728.63  4934.7 1729.32  4974.9 1725.10  4993.0 1724.97
  4993.2 1724.47  4996.7 1724.47  4997.0 1724.97  5025.1 1725.01  5085.2 1726.51
  5095.3 1728.08  5115.3 1728.54  5125.4 1729.66  5130.4 1731.18  5135.4 1730.34
  5145.4 1731.29  5155.4 1731.15  5195.6 1733.07  5255.7 1734.61  5326.0 1737.63
#Mann=3,-1,0
  4723.9    0.05       0  4993.0    0.05       0  4997.0    0.05       0
Bank Sta=4993,4997
Exp/Cntr=0.3,0.1

Type RM Length L Ch R = 1,1497,349,349,349
BEGIN DESCRIPTION:
Elm 02 07 1497.399
END DESCRIPTION:
XS GIS Cut Line= 3
      1600254.98      6834738.01      1599971.11      6834855.17
      1600054.99      6835437.96
#Sta/Elev= 30
  4692.9 1747.36  4702.1 1746.64  4725.3 1741.14  4736.9 1736.80  4755.4 1732.97
  4790.2 1730.88  4838.0 1729.63  4855.2 1727.63  4861.9 1725.55  4867.3 1725.37
  4885.8 1722.21  4952.5 1722.05  4968.4 1723.13  4974.2 1721.83  4983.0 1721.30
  4983.2 1720.80  4987.0 1721.30  4997.2 1722.62  5013.0 1722.50  5033.2 1723.48
  5130.9 1722.98  5154.4 1724.62  5184.7 1725.56  5215.0 1728.44  5255.4 1729.69
  5271.8 1730.97  5396.9 1731.51  5457.5 1733.28  5548.4 1734.54  5588.8 1741.51
#Mann=3,-1,0
  4692.9    0.05       0  4983.0    0.05       0  4987.0    0.05       0
Bank Sta=4983,4987
Exp/Cntr=0.3,0.1

Type RM Length L Ch R = 1,1148,404,404,404
BEGIN DESCRIPTION:
Mapping XS fcdd7cda
END DESCRIPTION:
XS GIS Cut Line= 4
      1600226.10      6834160.69      1599749.56      6834720.57
      1599684.45      6835061.71      1599684.45      6835480.98
#Sta/Elev= 30
  4468.9 1750.99  4510.3 1745.29  4524.5 1744.54  4531.1 1742.96  4537.6 1742.76
  4545.4 1740.28  4577.2 1736.42  4595.9 1734.35  4602.5 1732.56  4645.3 1728.48
  4651.9 1726.92  4680.5 1724.82  4915.6 1721.43  4998.0 1719.95  4998.3 1719.45
  5002.0 1719.95  5170.3 1722.14  5256.3 1721.38  5303.9 1722.84  5331.5 1722.91
  5354.2 1723.35  5425.5 1720.82  5596.2 1722.02  5647.7 1721.88  5727.7 1727.72
  5807.7 1729.36  5887.7 1732.49  5927.7 1736.43  5957.7 1743.29  5970.7 1744.40
#Mann=8,-1,0
  4468.9    0.12       0  4577.2    0.05       0  4915.6    0.12       0
  4998.0    0.07       0  5002.0    0.12       0  5303.9    0.05       0
  5331.5    0.12       0  5596.2    0.05       0
Bank Sta=4998,5002
Exp/Cntr=0.3,0.1

Type RM Length L Ch R = 1,744,0,0,0
BEGIN DESCRIPTION:
Elm 02 07 1011.348
END DESCRIPTION:
XS GIS Cut Line= 3
      1600077.65      6834027.87      1599562.06      6834259.63
      1599473.54      6835483.25
#Sta/Elev= 30
  4122.1 1745.63  4138.0 1744.07  4155.7 1739.98  4161.2 1739.70  4190.8 1731.61
  4230.7 1725.69  4265.2 1723.21  4284.4 1723.03  4374.0 1722.42  4776.0 1720.51
  4836.1 1717.92  4904.1 1717.18  4904.3 1717.18  4904.6 1716.68  4908.3 1717.18
  5026.6 1717.38  5056.7 1719.20  5076.8 1718.79  5096.8 1719.92  5152.5 1720.57
  5266.3 1721.23  5351.9 1719.94  5447.7 1718.52  5638.2 1719.67  5718.4 1726.08
  5788.6 1727.93  5824.2 1730.62  5829.2 1729.96  5868.8 1735.85  5914.2 1746.21
#Mann=9,-1,0
  4122.1    0.05       0  4265.2    0.12       0  4284.4    0.05       0
  4374.0    0.12       0  4904.1    0.05       0  4904.3    0.05       0
  4908.3    0.05       0  5152.5    0.12       0  5351.9    0.05       0
Bank Sta=4904.3,4908.3
Exp/Cntr=0.3,0.1

Chan Stop Cuts=-1