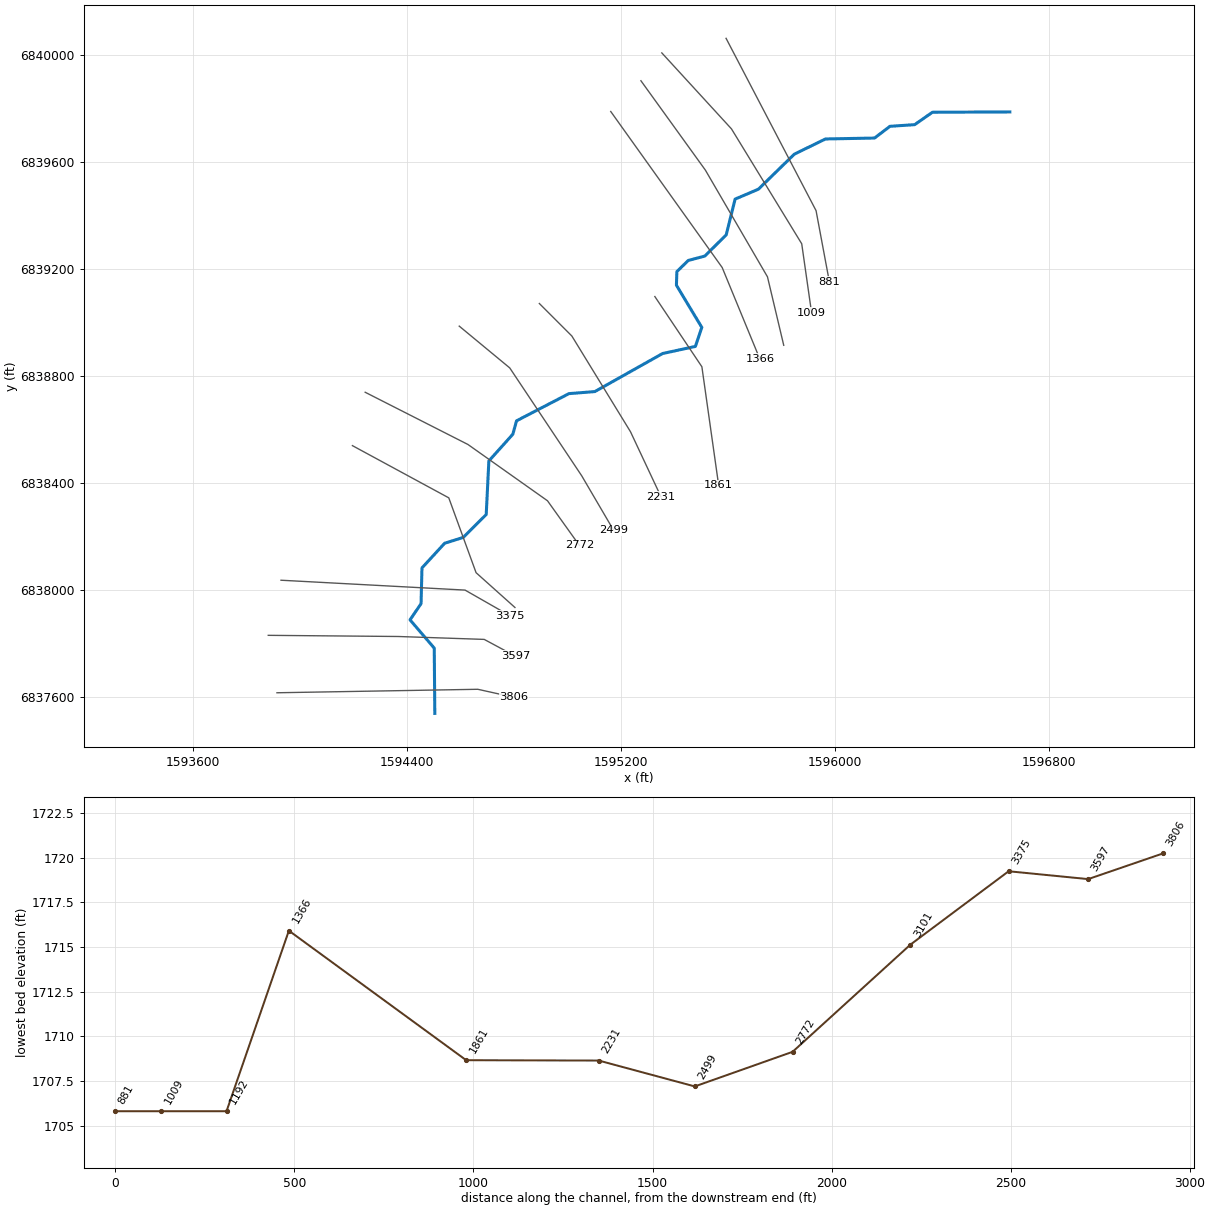
--- Elm 02 08.prj (project) ---

Proj Title=Elm 02 08 Base Level Engineering
Current Plan=p01
Default Exp/Contr=0.3,0.1
English Units
Geom File=g01
Flow File=f01
Plan File=p01
BEGIN DESCRIPTION:
Elm 02 08
END DESCRIPTION:

--- Elm 02 08.p01 (plan) ---

Plan Title=Multiple Run
Short Identifier=Multiple
Geom File=g01
Flow File=f01
Subcritical Flow
K Sum by GR= 0
Std Step Tol= 0.01
Critical Tol= 0.01
Num of Std Step Trials= 20
Max Error Tol= 0.3
Flow Tol Ratio= 0.001
Split Flow NTrial= 30
Split Flow Tol= 0.02
Split Flow Ratio= 0.02
Log Output Level= 0
Friction Slope Method= 1
Unsteady Friction Slope Method= 2
Unsteady Bridges Friction Slope Method= 1
Parabolic Critical Depth
Global Vel Dist=  1 , 1 , 1
Global Log Level= 0
CheckData=True
Encroach Param= -1, 0, 0, 0
BEGIN DESCRIPTION:
Multiple Run
END DESCRIPTION:

--- Elm 02 08.f01 (steady flow) ---

Flow Title=Multiple
Number of Profiles=7
Profile Names=10-year,25-year,50-year,1pct_min,100-year,1pct_plu,500-year
River Rch & RM= Elm 02 08,Reach-1,3806
     141     186     222     164     262     361     371
Boundary for River Rch & Prof#=Elm 02 08,Reach-1,1
Up Type=0
Dn Type=3
Dn Slope=0.001
Boundary for River Rch & Prof#=Elm 02 08,Reach-1,2
Up Type=0
Dn Type=3
Dn Slope=0.001
Boundary for River Rch & Prof#=Elm 02 08,Reach-1,3
Up Type=0
Dn Type=3
Dn Slope=0.001
Boundary for River Rch & Prof#=Elm 02 08,Reach-1,4
Up Type=0
Dn Type=3
Dn Slope=0.001
Boundary for River Rch & Prof#=Elm 02 08,Reach-1,5
Up Type=0
Dn Type=3
Dn Slope=0.001
Boundary for River Rch & Prof#=Elm 02 08,Reach-1,6
Up Type=0
Dn Type=3
Dn Slope=0.001
Boundary for River Rch & Prof#=Elm 02 08,Reach-1,7
Up Type=0
Dn Type=3
Dn Slope=0.001

--- Elm 02 08.g01 (geometry) ---

Geom Title=Existing Conditions

River Reach=Elm 02 08,Reach-1
Reach XY= 30
      1594505.00      6837538.00      1594502.93      6837782.15
      1594412.33      6837887.90      1594453.60      6837948.44
      1594457.06      6838082.15      1594541.76      6838174.38
      1594611.07      6838196.15      1594697.20      6838281.79
      1594707.07      6838482.15      1594796.70      6838582.26
      1594810.61      6838632.41      1595006.58      6838734.17
      1595103.42      6838741.83      1595356.59      6838884.17
      1595479.15      6838910.72      1595503.26      6838981.84
      1595408.30      6839139.76      1595409.98      6839190.55
      1595452.39      6839232.25      1595514.68      6839248.78
      1595594.49      6839328.19      1595627.72      6839461.89
      1595714.66      6839498.79      1595848.94      6839629.86
      1595965.50      6839686.80      1596149.06      6839690.26
      1596206.60      6839734.14      1596299.02      6839740.36
      1596365.50      6839786.78      1596655.00      6839788.00

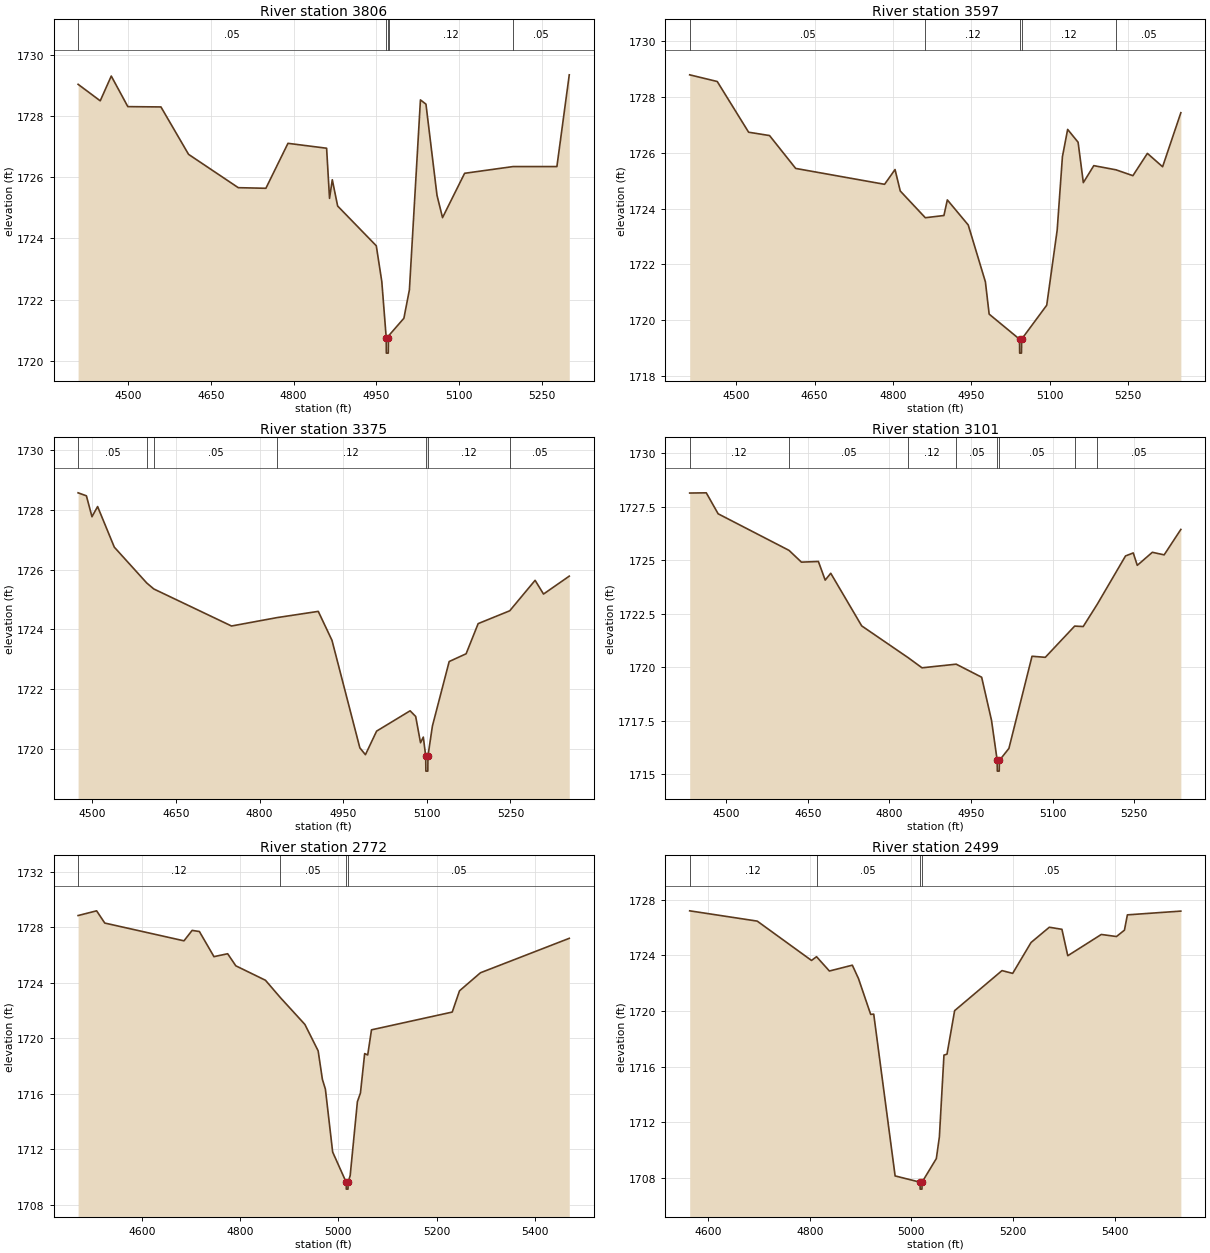
Type RM Length L Ch R = 1,3806,209,209,209
BEGIN DESCRIPTION:
Elm 02 08 2.0
END DESCRIPTION:
XS GIS Cut Line= 3
      1593914.89      6837615.10      1594665.79      6837628.12
      1594801.27      6837598.01
#Sta/Elev= 30
  4409.6 1729.04  4449.7 1728.50  4469.7 1729.31  4499.7 1728.31  4559.7 1728.30
  4609.7 1726.75  4699.8 1725.66  4749.8 1725.64  4789.8 1727.11  4859.8 1726.95
  4865.1 1725.31  4870.1 1725.92  4879.8 1725.06  4949.8 1723.76  4959.8 1722.59
  4967.8 1720.75  4968.0 1720.25  4971.5 1720.25  4971.8 1720.75  4973.3 1720.84
  4999.8 1721.39  5009.8 1722.32  5029.8 1728.53  5039.8 1728.39  5059.8 1725.41
  5069.8 1724.68  5109.8 1726.13  5197.5 1726.35  5277.0 1726.35  5299.4 1729.35
#Mann=5,-1,0
  4409.6    0.05       0  4967.8    0.07       0  4971.8    0.05       0
  4973.3    0.12       0  5197.5    0.05       0
Bank Sta=4967.8,4971.8
Exp/Cntr=0.3,0.1

Type RM Length L Ch R = 1,3597,222,222,222
BEGIN DESCRIPTION:
Mapping XS 9cb1e8bc
END DESCRIPTION:
XS GIS Cut Line= 4
      1593882.34      6837829.94      1594368.48      6837825.60
      1594689.66      6837814.75      1594805.75      6837752.40
#Sta/Elev= 30
  4411.3 1728.80  4464.0 1728.56  4524.0 1726.74  4564.0 1726.62  4614.0 1725.44
  4784.0 1724.87  4804.0 1725.40  4814.0 1724.63  4861.9 1723.67  4897.5 1723.75
  4904.0 1724.31  4944.0 1723.41  4976.8 1721.37  4984.0 1720.21  5042.1 1719.31
  5042.3 1718.81  5045.8 1718.81  5046.1 1719.31  5094.1 1720.53  5114.1 1723.23
  5124.1 1725.86  5134.1 1726.84  5154.1 1726.38  5164.1 1724.93  5184.1 1725.54
  5226.6 1725.39  5258.9 1725.18  5286.6 1725.98  5315.7 1725.50  5350.6 1727.44
#Mann=5,-1,0
  4411.3    0.05       0  4861.9    0.12       0  5042.1    0.07       0
  5046.1    0.12       0  5226.6    0.05       0
Bank Sta=5042.1,5046.1
Exp/Cntr=0.3,0.1

Type RM Length L Ch R = 1,3375,274,274,274
BEGIN DESCRIPTION:
Mapping XS ed8edcc2
END DESCRIPTION:
XS GIS Cut Line= 3
      1593930.09      6838036.11      1594618.05      6837999.21
      1594785.15      6837903.73
#Sta/Elev= 30
  4474.2 1728.57  4489.1 1728.47  4499.1 1727.77  4509.2 1728.11  4539.2 1726.75
  4597.4 1725.55  4610.1 1725.35  4749.5 1724.11  4830.8 1724.39  4905.2 1724.60
  4929.8 1723.63  4979.8 1720.03  4989.8 1719.80  5009.9 1720.59  5070.0 1721.27
  5080.0 1721.08  5088.7 1720.20  5093.7 1720.39  5098.0 1719.75  5098.3 1719.25
  5101.8 1719.25  5102.0 1719.75  5110.0 1720.76  5140.1 1722.92  5170.5 1723.18
  5192.1 1724.19  5248.8 1724.62  5294.3 1725.64  5309.4 1725.18  5355.6 1725.78
#Mann=7,-1,0
  4474.2    0.05       0  4597.4    0.12       0  4610.1    0.05       0
  4830.8    0.12       0  5098.0    0.07       0  5102.0    0.12       0
  5248.8    0.05       0
Bank Sta=5098,5102
Exp/Cntr=0.3,0.1

Type RM Length L Ch R = 1,3101,329,329,329
BEGIN DESCRIPTION:
Mapping XS e4e48c57
END DESCRIPTION:
XS GIS Cut Line= 4
      1594197.02      6838539.59      1594557.28      6838344.26
      1594659.28      6838064.32      1594804.65      6837934.13
#Sta/Elev= 30
  4432.7 1728.14  4463.2 1728.15  4485.0 1727.17  4615.3 1725.46  4638.1 1724.91
  4669.3 1724.94  4681.8 1724.07  4692.0 1724.39  4748.9 1721.93  4834.5 1720.44
  4859.8 1719.97  4922.6 1720.14  4969.4 1719.53  4987.5 1717.52  4998.0 1715.64
  4998.2 1715.14  5001.7 1715.14  5002.0 1715.64  5019.5 1716.20  5062.0 1720.51
  5086.4 1720.46  5140.4 1721.92  5156.1 1721.90  5181.9 1722.94  5233.9 1725.20
  5248.1 1725.34  5255.5 1724.76  5283.2 1725.37  5304.9 1725.25  5335.6 1726.44
#Mann=8,-1,0
  4432.7    0.12       0  4615.3    0.05       0  4834.5    0.12       0
  4922.6    0.05       0  4998.0    0.03       0  5002.0    0.05       0
  5140.4    0.12       0  5181.9    0.05       0
Bank Sta=4998,5002
Exp/Cntr=0.3,0.1

Type RM Length L Ch R = 1,2772,273,273,273
BEGIN DESCRIPTION:
Mapping XS ed7bbbec
END DESCRIPTION:
XS GIS Cut Line= 4
      1594244.74      6838739.25      1594628.90      6838543.92
      1594926.21      6838333.41      1595045.56      6838166.32
#Sta/Elev= 30
  4469.8 1728.83  4507.5 1729.17  4524.1 1728.29  4685.5 1727.01  4702.1 1727.76
  4716.9 1727.68  4746.6 1725.87  4774.5 1726.08  4791.1 1725.21  4851.5 1724.17
  4881.4 1722.94  4931.8 1720.99  4958.8 1719.09  4967.5 1717.03  4973.6 1716.33
  4988.4 1711.80  5015.9 1709.63  5016.2 1709.13  5019.7 1709.13  5019.9 1709.63
  5024.1 1710.11  5038.8 1715.43  5045.0 1716.05  5053.6 1718.89  5059.8 1718.79
  5067.5 1720.60  5232.0 1721.88  5246.8 1723.41  5289.5 1724.71  5470.4 1727.19
#Mann=4,-1,0
  4469.8    0.12       0  4881.4    0.05       0  5015.9    0.03       0
  5019.9    0.05       0
Bank Sta=5015.9,5019.9
Exp/Cntr=0.3,0.1

Type RM Length L Ch R = 1,2499,268,268,268
BEGIN DESCRIPTION:
Mapping XS 46761efa
END DESCRIPTION:
XS GIS Cut Line= 4
      1594596.32      6838986.64      1594785.15      6838830.38
      1595054.24      6838426.73      1595173.52      6838222.88
#Sta/Elev= 30
  4563.9 1727.21  4696.8 1726.47  4803.6 1723.64  4813.5 1723.91  4838.8 1722.88
  4883.9 1723.30  4896.0 1722.34  4920.0 1719.76  4926.0 1719.78  4968.1 1708.14
  5017.1 1707.69  5017.4 1707.19  5020.9 1707.19  5021.1 1707.69  5049.2 1709.39
  5055.2 1710.95  5064.2 1716.83  5070.2 1716.90  5085.2 1720.03  5178.4 1722.91
  5199.4 1722.71  5235.5 1724.93  5271.5 1726.03  5296.3 1725.88  5307.8 1723.98
  5373.8 1725.51  5403.6 1725.36  5419.3 1725.82  5425.1 1726.92  5530.3 1727.19
#Mann=4,-1,0
  4563.9    0.12       0  4813.5    0.05       0  5017.1    0.03       0
  5021.1    0.05       0
Bank Sta=5017.1,5021.1
Exp/Cntr=0.3,0.1

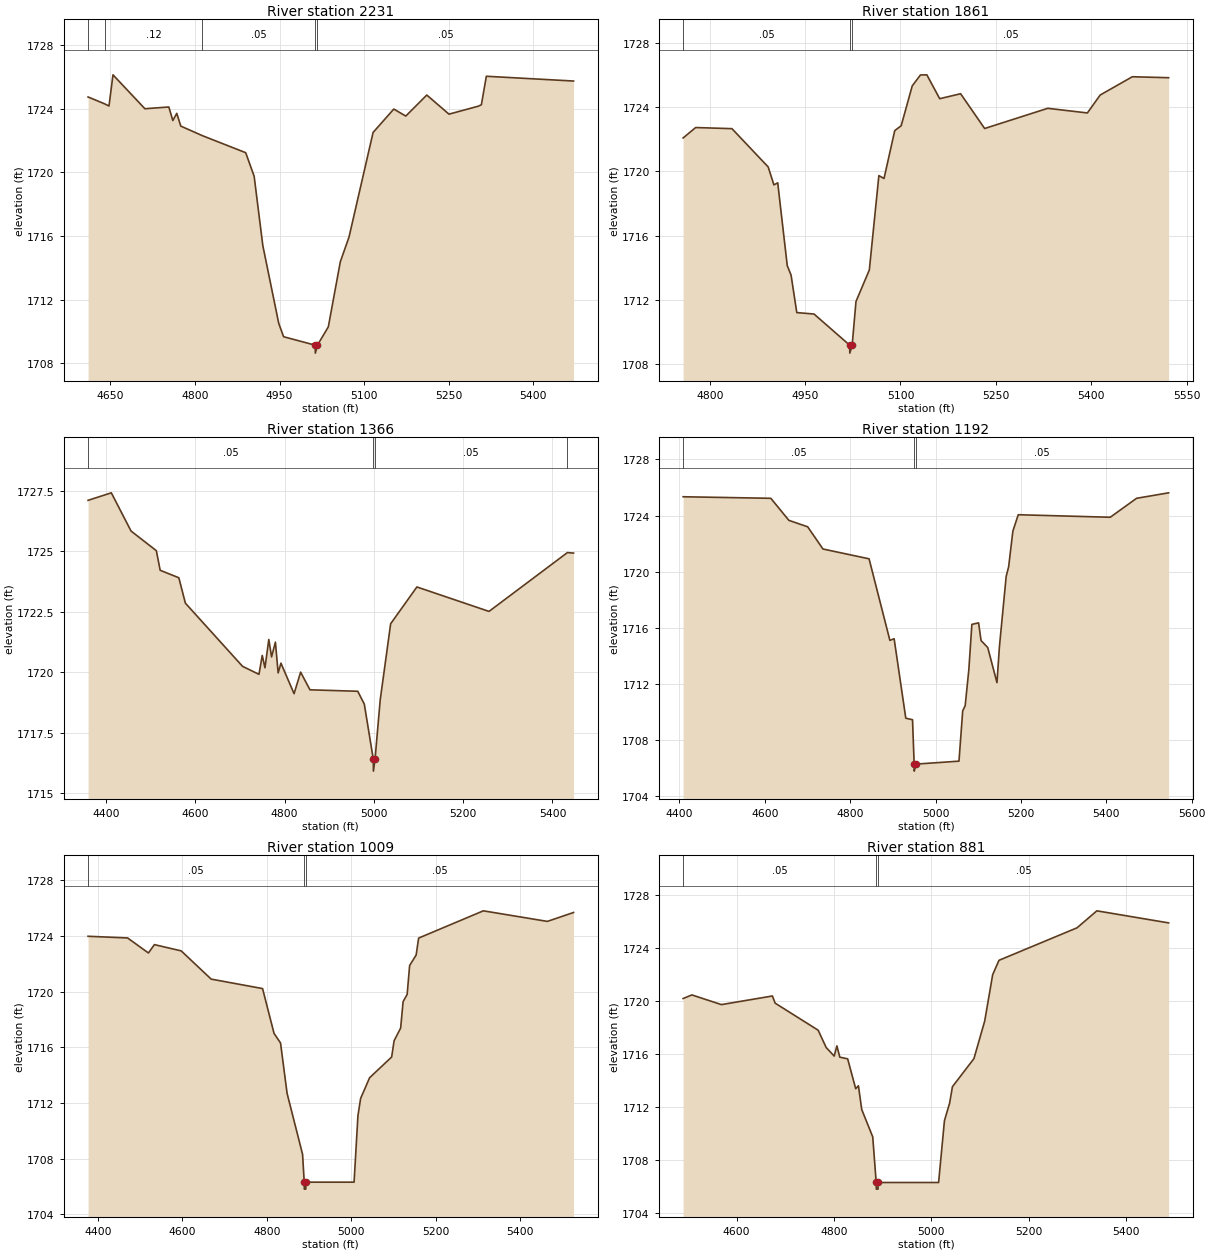
Type RM Length L Ch R = 1,2231,370,370,370
BEGIN DESCRIPTION:
Mapping XS c0263dcf
END DESCRIPTION:
XS GIS Cut Line= 4
      1594895.79      6839071.29      1595017.35      6838949.73
      1595236.54      6838591.66      1595350.79      6838348.07
#Sta/Elev= 30
  4610.5 1724.73  4639.8 1724.30  4647.6 1724.16  4654.7 1726.12  4711.3 1723.99
  4753.7 1724.10  4760.8 1723.25  4767.8 1723.70  4774.9 1722.90  4813.1 1722.30
  4890.0 1721.23  4905.0 1719.75  4920.4 1715.39  4948.6 1710.51  4957.2 1709.67
  5013.2 1709.14  5013.5 1708.64  5017.2 1709.14  5036.5 1710.29  5057.8 1714.38
  5073.2 1715.93  5115.9 1722.50  5152.6 1723.97  5173.9 1723.53  5211.1 1724.85
  5250.5 1723.65  5302.4 1724.15  5307.9 1724.24  5316.7 1726.03  5471.3 1725.73
#Mann=5,-1,0
  4610.5    0.05       0  4639.8    0.12       0  4813.1    0.05       0
  5013.2    0.03       0  5017.2    0.05       0
Bank Sta=5013.2,5017.2
Exp/Cntr=0.3,0.1

Type RM Length L Ch R = 1,1861,495,495,495
BEGIN DESCRIPTION:
Mapping XS e4921392
END DESCRIPTION:
XS GIS Cut Line= 3
      1595327.66      6839097.33      1595503.46      6838834.72
      1595566.17      6838391.46
#Sta/Elev= 30
  4758.1 1722.09  4777.8 1722.74  4834.9 1722.67  4891.9 1720.28  4900.9 1719.16
  4906.9 1719.29  4921.9 1714.12  4927.9 1713.53  4936.9 1711.19  4964.0 1711.10
  5020.0 1709.16  5020.3 1708.66  5024.0 1709.16  5030.0 1711.88  5051.0 1713.85
  5066.0 1719.74  5074.1 1719.56  5091.0 1722.55  5101.1 1722.85  5118.5 1725.34
  5131.4 1726.02  5141.5 1726.03  5161.7 1724.54  5194.6 1724.85  5232.4 1722.68
  5331.7 1723.94  5394.0 1723.65  5414.2 1724.77  5464.7 1725.91  5521.8 1725.85
#Mann=3,-1,0
  4758.1    0.05       0  5020.0    0.03       0  5024.0    0.05       0
Bank Sta=5020,5024
Exp/Cntr=0.3,0.1

Type RM Length L Ch R = 1,1366,174,174,174
BEGIN DESCRIPTION:
Mapping XS 7c767574
END DESCRIPTION:
XS GIS Cut Line= 3
      1595162.73      6839789.60      1595579.42      6839205.81
      1595720.21      6838863.58
#Sta/Elev= 30
  4359.9 1727.11  4412.0 1727.42  4456.2 1725.84  4512.8 1725.03  4521.4 1724.22
  4563.2 1723.91  4577.9 1722.86  4705.9 1720.25  4742.7 1719.92  4750.0 1720.70
  4756.1 1720.19  4764.7 1721.36  4770.9 1720.64  4779.5 1721.25  4785.6 1719.98
  4791.9 1720.38  4821.3 1719.12  4836.0 1720.01  4856.9 1719.28  4963.9 1719.22
  4978.6 1718.69  4998.7 1716.42  4999.0 1715.92  5002.7 1716.42  5014.2 1718.86
  5037.6 1722.01  5096.4 1723.53  5257.9 1722.52  5433.4 1724.95  5447.2 1724.93
#Mann=4,-1,0
  4359.9    0.05       0  4998.7    0.05       0  5002.7    0.05       0
  5433.4   0.075       0
Bank Sta=4998.7,5002.7
Exp/Cntr=0.3,0.1

Type RM Length L Ch R = 1,1192,183,183,183
BEGIN DESCRIPTION:
Mapping XS 017641bf
END DESCRIPTION:
XS GIS Cut Line= 4
      1595275.59      6839904.61      1595516.48      6839570.39
      1595748.69      6839171.09      1595809.46      6838914.99
#Sta/Elev= 30
  4408.9 1725.34  4614.3 1725.23  4656.6 1723.66  4700.6 1723.20  4736.4 1721.62
  4844.4 1720.92  4893.2 1715.11  4903.1 1715.23  4930.4 1709.57  4946.2 1709.46
  4950.0 1706.30  4950.2 1705.80  4954.0 1706.30  5055.0 1706.51  5063.7 1710.09
  5069.5 1710.46  5078.1 1713.03  5085.2 1716.25  5100.9 1716.36  5106.7 1715.10
  5122.4 1714.60  5144.0 1712.10  5149.7 1714.65  5165.5 1719.66  5171.3 1720.35
  5181.2 1722.89  5193.8 1724.06  5409.3 1723.88  5471.0 1725.23  5546.0 1725.62
#Mann=3,-1,0
  4408.9    0.05       0  4950.0    0.03       0  4954.0    0.05       0
Bank Sta=4950,4954
Exp/Cntr=0.3,0.1

Type RM Length L Ch R = 1,1009,128,128,128
BEGIN DESCRIPTION:
Mapping XS 2afd681b
END DESCRIPTION:
XS GIS Cut Line= 4
      1595353.74      6840008.74      1595614.14      6839724.47
      1595876.73      6839294.78      1595913.61      6839036.58
#Sta/Elev= 30
  4376.8 1723.98  4470.4 1723.86  4519.8 1722.78  4533.9 1723.38  4597.4 1722.93
  4668.4 1720.90  4790.1 1720.22  4817.3 1717.00  4832.7 1716.31  4848.2 1712.69
  4884.9 1708.30  4888.8 1706.30  4889.0 1705.80  4892.5 1705.80  4892.8 1706.30
  5006.9 1706.30  5016.0 1711.07  5022.4 1712.32  5043.7 1713.81  5095.9 1715.30
  5101.7 1716.47  5117.2 1717.38  5123.0 1719.28  5132.6 1719.80  5138.5 1721.88
  5153.9 1722.63  5159.8 1723.85  5313.1 1725.81  5464.7 1725.05  5526.7 1725.69
#Mann=3,-1,0
  4376.8    0.05       0  4888.8    0.05       0  4892.8    0.05       0
Bank Sta=4888.8,4892.8
Exp/Cntr=0.3,0.1

Type RM Length L Ch R = 1,881,0,0,0
BEGIN DESCRIPTION:
Elm 02 08 1.0
END DESCRIPTION:
XS GIS Cut Line= 3
      1595593.94      6840063.27      1595930.33      6839418.70
      1595980.00      6839153.07
#Sta/Elev= 30
  4490.1 1720.17  4508.1 1720.44  4568.7 1719.71  4673.5 1720.36  4679.1 1719.82
  4767.5 1717.78  4783.9 1716.48  4800.4 1715.83  4806.0 1716.60  4811.9 1715.75
  4828.1 1715.62  4844.6 1713.37  4850.2 1713.59  4857.0 1711.80  4879.6 1709.74
  4886.7 1706.30  4887.0 1705.80  4890.5 1705.80  4890.7 1706.30  5014.9 1706.30
  5026.9 1710.96  5037.5 1712.28  5043.3 1713.52  5087.5 1715.64  5109.6 1718.47
  5126.0 1721.97  5139.0 1723.05  5299.3 1725.50  5340.0 1726.78  5487.4 1725.87
#Mann=3,-1,0
  4490.1    0.05       0  4886.7    0.03       0  4890.7    0.05       0
Bank Sta=4886.7,4890.7
Exp/Cntr=0.3,0.1

Chan Stop Cuts=-1