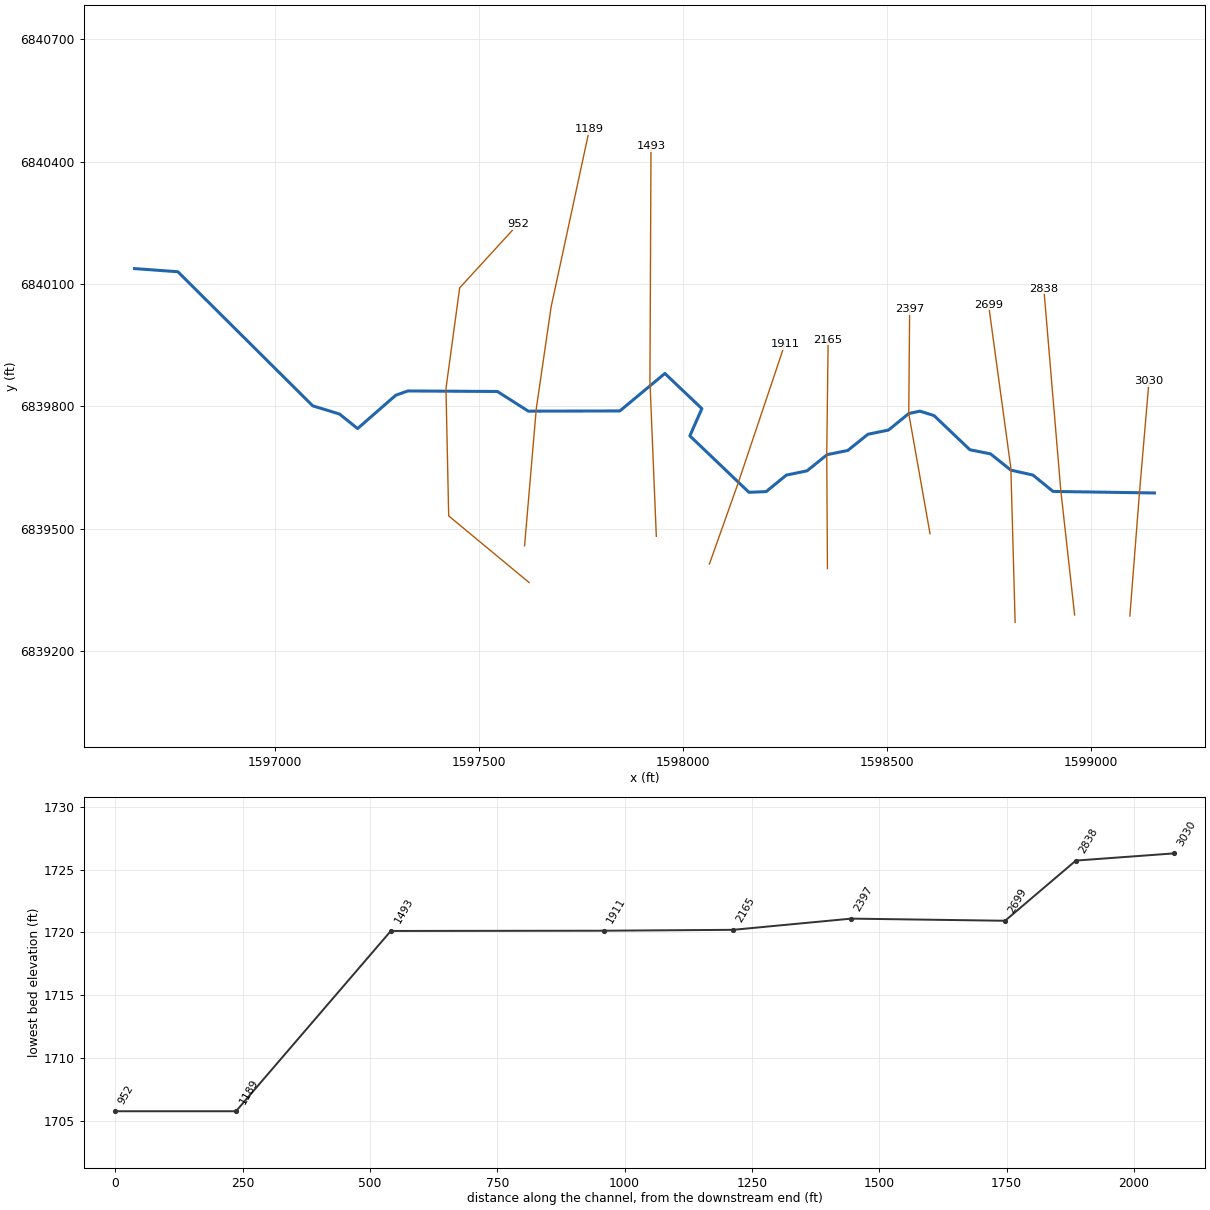
--- Elm 02 09.prj (project) ---

Proj Title=Elm 02 09 Base Level Engineering
Current Plan=p01
Default Exp/Contr=0.3,0.1
English Units
Geom File=g01
Flow File=f01
Plan File=p01
BEGIN DESCRIPTION:
Elm 02 09
END DESCRIPTION:

--- Elm 02 09.p01 (plan) ---

Plan Title=Multiple Run
Short Identifier=Multiple
Geom File=g01
Flow File=f01
Subcritical Flow
K Sum by GR= 0
Std Step Tol= 0.01
Critical Tol= 0.01
Num of Std Step Trials= 20
Max Error Tol= 0.3
Flow Tol Ratio= 0.001
Split Flow NTrial= 30
Split Flow Tol= 0.02
Split Flow Ratio= 0.02
Log Output Level= 0
Friction Slope Method= 1
Unsteady Friction Slope Method= 2
Unsteady Bridges Friction Slope Method= 1
Parabolic Critical Depth
Global Vel Dist=  1 , 1 , 1
Global Log Level= 0
CheckData=True
Encroach Param= -1, 0, 0, 0
BEGIN DESCRIPTION:
Multiple Run
END DESCRIPTION:

--- Elm 02 09.f01 (steady flow) ---

Flow Title=Multiple
Number of Profiles=7
Profile Names=10-year,25-year,50-year,1pct_min,100-year,1pct_plu,500-year
River Rch & RM= Elm 02 09,Reach-1,3030
     120     158     187     138     222     305     313
Boundary for River Rch & Prof#=Elm 02 09,Reach-1,1
Up Type=0
Dn Type=3
Dn Slope=0.001
Boundary for River Rch & Prof#=Elm 02 09,Reach-1,2
Up Type=0
Dn Type=3
Dn Slope=0.001
Boundary for River Rch & Prof#=Elm 02 09,Reach-1,3
Up Type=0
Dn Type=3
Dn Slope=0.001
Boundary for River Rch & Prof#=Elm 02 09,Reach-1,4
Up Type=0
Dn Type=3
Dn Slope=0.001
Boundary for River Rch & Prof#=Elm 02 09,Reach-1,5
Up Type=0
Dn Type=3
Dn Slope=0.001
Boundary for River Rch & Prof#=Elm 02 09,Reach-1,6
Up Type=0
Dn Type=3
Dn Slope=0.001
Boundary for River Rch & Prof#=Elm 02 09,Reach-1,7
Up Type=0
Dn Type=3
Dn Slope=0.001

--- Elm 02 09.g01 (geometry) ---

Geom Title=Existing Conditions

River Reach=Elm 02 09,Reach-1
Reach XY= 30
      1599155.00      6839588.00      1598906.55      6839591.75
      1598857.18      6839631.88      1598802.80      6839644.08
      1598753.26      6839683.81      1598702.71      6839693.85
      1598614.67      6839777.79      1598580.03      6839788.50
      1598552.81      6839782.69      1598503.28      6839742.22
      1598452.80      6839731.92      1598403.28      6839692.16
      1598352.80      6839681.92      1598303.28      6839642.16
      1598252.80      6839631.84      1598203.26      6839591.31
      1598161.03      6839589.61      1598016.24      6839728.00
      1598045.70      6839794.70      1597955.03      6839880.92
      1597844.57      6839789.06      1597620.22      6839788.52
      1597544.50      6839836.78      1597324.98      6839838.03
      1597295.20      6839827.48      1597201.77      6839745.84
      1597157.29      6839781.57      1597091.79      6839801.60
      1596761.22      6840130.26      1596655.00      6840138.00

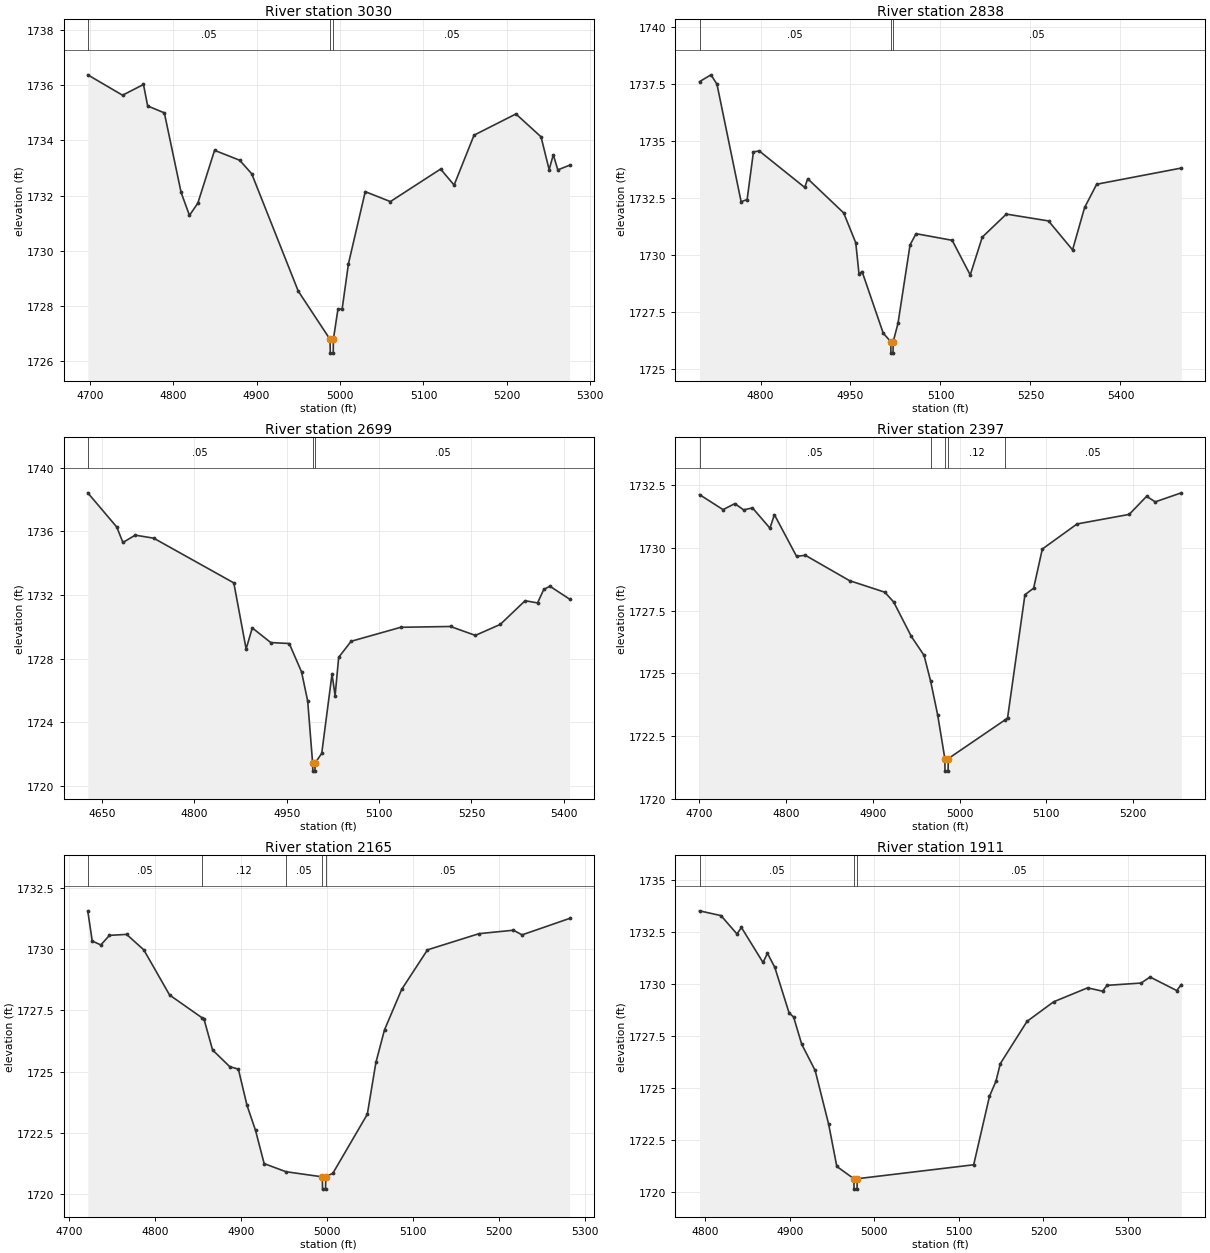
Type RM Length L Ch R = 1,3030,192,192,192
BEGIN DESCRIPTION:
Elm 02 09 2846.631
END DESCRIPTION:
XS GIS Cut Line= 3
      1599094.81      6839286.45      1599118.27      6839587.94
      1599141.70      6839862.04
#Sta/Elev= 30
  4697.6 1736.38  4739.3 1735.64  4764.4 1736.03  4769.4 1735.25  4789.4 1735.00
  4809.5 1732.11  4819.5 1731.28  4829.5 1731.72  4849.6 1733.64  4879.7 1733.28
  4894.1 1732.79  4949.9 1728.53  4988.0 1726.78  4988.3 1726.28  4991.8 1726.28
  4992.0 1726.78  4997.5 1727.88  5002.5 1727.88  5010.1 1729.53  5030.2 1732.14
  5060.3 1731.78  5120.5 1732.96  5136.7 1732.38  5160.6 1734.19  5210.8 1734.96
  5240.9 1734.13  5250.6 1732.94  5255.6 1733.48  5261.0 1732.93  5275.1 1733.10
#Mann=3,-1,0
  4697.6    0.05       0  4988.0    0.03       0  4992.0    0.05       0
Bank Sta=4988,4992
Exp/Cntr=0.3,0.1

Type RM Length L Ch R = 1,2838,139,139,139
BEGIN DESCRIPTION:
Elm 02 09 2837.78
END DESCRIPTION:
XS GIS Cut Line= 3
      1598959.41      6839289.05      1598925.55      6839593.79
      1598883.88      6840088.63
#Sta/Elev= 30
  4698.3 1737.62  4717.4 1737.92  4727.4 1737.51  4767.7 1732.35  4777.7 1732.45
  4788.2 1734.54  4797.9 1734.58  4873.7 1732.98  4878.7 1733.36  4938.7 1731.86
  4958.8 1730.55  4964.2 1729.18  4969.3 1729.29  5004.5 1726.59  5017.2 1726.21
  5017.4 1725.71  5020.9 1725.71  5021.2 1726.21  5029.2 1727.02  5049.3 1730.46
  5059.3 1730.95  5119.5 1730.66  5149.6 1729.14  5169.7 1730.80  5209.8 1731.81
  5280.1 1731.51  5320.2 1730.24  5340.3 1732.10  5360.4 1733.12  5501.5 1733.83
#Mann=3,-1,0
  4698.3    0.05       0  5017.2    0.05       0  5021.2    0.05       0
Bank Sta=5017.2,5021.2
Exp/Cntr=0.3,0.1

Type RM Length L Ch R = 1,2699,302,302,302
BEGIN DESCRIPTION:
Elm 02 09 2699.17
END DESCRIPTION:
XS GIS Cut Line= 3
      1598813.57      6839270.91      1598803.15      6839648.47
      1598748.46      6840049.56
#Sta/Elev= 30
  4626.8 1738.42  4673.9 1736.27  4683.9 1735.30  4703.9 1735.76  4733.9 1735.57
  4864.0 1732.76  4884.0 1728.61  4894.0 1729.93  4924.0 1729.01  4954.0 1728.95
  4974.0 1727.17  4984.0 1725.33  4992.0 1721.43  4992.3 1720.93  4995.8 1720.93
  4996.0 1721.43  5006.8 1722.05  5023.5 1727.03  5028.5 1725.67  5034.3 1728.08
  5054.5 1729.09  5135.2 1729.97  5216.0 1730.02  5256.3 1729.46  5296.7 1730.15
  5337.1 1731.64  5357.3 1731.50  5367.4 1732.35  5377.4 1732.55  5409.3 1731.74
#Mann=3,-1,0
  4626.8    0.05       0  4992.0    0.03       0  4996.0    0.05       0
Bank Sta=4992,4996
Exp/Cntr=0.3,0.1

Type RM Length L Ch R = 1,2397,232,232,232
BEGIN DESCRIPTION:
Elm 02 09 2397.084
END DESCRIPTION:
XS GIS Cut Line= 3
      1598605.00      6839487.97      1598552.81      6839782.69
      1598555.00      6840037.98
#Sta/Elev= 30
  4700.7 1732.12  4727.8 1731.52  4741.4 1731.76  4751.5 1731.51  4761.7 1731.59
  4781.8 1730.78  4786.9 1731.32  4812.4 1729.66  4822.6 1729.70  4873.4 1728.69
  4914.0 1728.23  4924.2 1727.84  4944.5 1726.47  4959.2 1725.71  4966.7 1724.69
  4974.9 1723.33  4983.1 1721.60  4983.3 1721.10  4986.8 1721.10  4987.1 1721.60
  5051.9 1723.13  5055.3 1723.22  5075.3 1728.13  5085.3 1728.39  5095.3 1729.95
  5135.3 1730.95  5195.3 1731.33  5215.3 1732.05  5225.3 1731.83  5255.3 1732.19
#Mann=5,-1,0
  4700.7    0.05       0  4966.7    0.12       0  4983.1    0.07       0
  4987.1    0.12       0  5051.9    0.05       0
Bank Sta=4983.1,4987.1
Exp/Cntr=0.3,0.1

Type RM Length L Ch R = 1,2165,254,254,254
BEGIN DESCRIPTION:
Elm 02 09 2165.27
END DESCRIPTION:
XS GIS Cut Line= 3
      1598353.50      6839402.79      1598351.76      6839682.33
      1598355.23      6839963.27
#Sta/Elev= 30
  4721.7 1731.55  4726.9 1730.32  4736.9 1730.16  4746.9 1730.55  4766.9 1730.59
  4786.9 1729.96  4816.9 1728.12  4854.3 1727.20  4856.9 1727.14  4866.9 1725.88
  4886.9 1725.20  4896.9 1725.10  4906.9 1723.63  4916.9 1722.60  4926.9 1721.25
  4952.2 1720.92  4994.6 1720.71  4994.8 1720.21  4998.3 1720.21  4998.6 1720.71
  5006.9 1720.86  5046.9 1723.26  5056.9 1725.37  5066.9 1726.70  5086.9 1728.35
  5116.9 1729.96  5176.9 1730.62  5216.9 1730.76  5226.9 1730.57  5282.2 1731.24
#Mann=5,-1,0
  4721.7    0.05       0  4854.3    0.12       0  4952.2    0.05       0
  4994.6    0.03       0  4998.6    0.05       0
Bank Sta=4994.6,4998.6
Exp/Cntr=0.3,0.1

Type RM Length L Ch R = 1,1911,418,418,418
BEGIN DESCRIPTION:
Elm 02 09 1911.16
END DESCRIPTION:
XS GIS Cut Line= 3
      1598064.20      6839414.05      1598134.53      6839612.02
      1598249.10      6839953.11
#Sta/Elev= 30
  4793.2 1733.51  4818.6 1733.28  4837.5 1732.40  4842.8 1732.71  4868.3 1731.03
  4873.6 1731.47  4882.3 1730.79  4899.2 1728.60  4904.5 1728.41  4914.1 1727.10
  4930.0 1725.84  4946.0 1723.25  4955.6 1721.23  4975.8 1720.64  4976.0 1720.14
  4979.5 1720.14  4979.8 1720.64  5117.5 1721.31  5136.2 1724.60  5143.8 1725.32
  5149.0 1726.17  5180.6 1728.20  5212.1 1729.14  5252.2 1729.81  5269.9 1729.65
  5275.2 1729.93  5315.5 1730.04  5326.1 1730.33  5357.7 1729.68  5363.1 1729.97
#Mann=3,-1,0
  4793.2    0.05       0  4975.8    0.03       0  4979.8    0.05       0
Bank Sta=4975.8,4979.8
Exp/Cntr=0.3,0.1

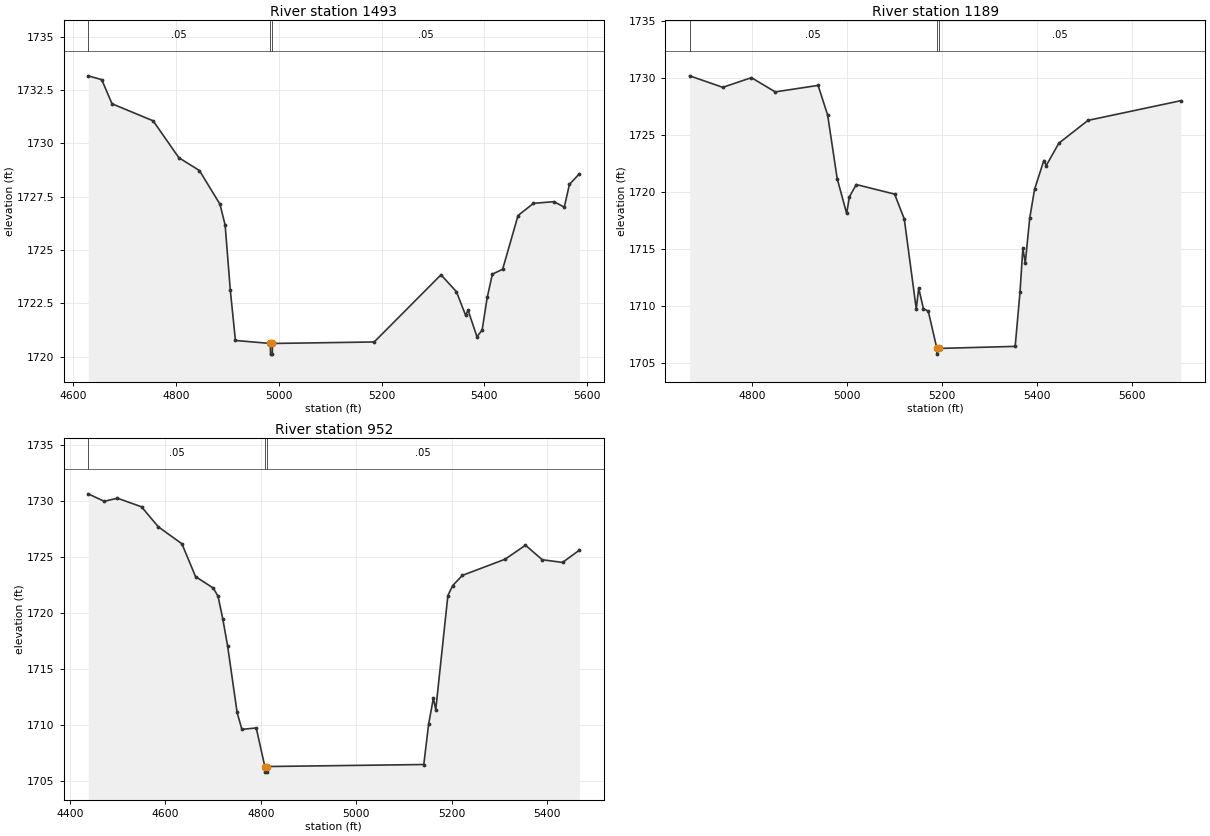
Type RM Length L Ch R = 1,1493,304,304,304
BEGIN DESCRIPTION:
Elm 02 09 1492.65
END DESCRIPTION:
XS GIS Cut Line= 3
      1597934.01      6839481.77      1597918.39      6839862.02
      1597920.99      6840437.54
#Sta/Elev= 30
  4629.1 1733.17  4655.4 1732.99  4675.4 1731.86  4755.4 1731.06  4805.5 1729.33
  4845.5 1728.73  4885.5 1727.15  4895.6 1726.17  4905.6 1723.13  4915.6 1720.76
  4983.6 1720.62  4983.9 1720.12  4987.4 1720.12  4987.6 1720.62  5185.7 1720.69
  5315.7 1723.84  5345.7 1723.05  5363.5 1721.95  5368.5 1722.17  5385.7 1720.94
  5395.7 1721.24  5405.7 1722.78  5415.7 1723.87  5435.7 1724.10  5465.7 1726.62
  5495.7 1727.19  5535.7 1727.27  5555.7 1727.01  5565.7 1728.08  5585.2 1728.58
#Mann=3,-1,0
  4629.1    0.05       0  4983.6    0.05       0  4987.6    0.05       0
Bank Sta=4983.6,4987.6
Exp/Cntr=0.3,0.1

Type RM Length L Ch R = 1,1189,237,237,237
BEGIN DESCRIPTION:
Elm 02 09 1188.55
END DESCRIPTION:
XS GIS Cut Line= 4
      1597611.09      6839458.37      1597639.74      6839794.31
      1597676.20      6840044.31      1597769.95      6840479.21
#Sta/Elev= 30
  4668.6 1730.22  4738.5 1729.21  4798.7 1730.06  4848.9 1728.81  4939.2 1729.38
  4959.3 1726.78  4979.4 1721.20  4999.4 1718.14  5005.1 1719.60  5019.6 1720.68
  5100.4 1719.84  5120.7 1717.66  5146.0 1709.76  5151.1 1711.58  5161.1 1709.78
  5171.2 1709.58  5189.4 1706.30  5189.6 1705.80  5193.4 1706.30  5354.3 1706.48
  5364.5 1711.24  5370.5 1715.10  5375.6 1713.80  5384.9 1717.71  5395.2 1720.27
  5414.7 1722.79  5419.8 1722.35  5446.3 1724.31  5507.7 1726.31  5703.3 1728.04
#Mann=3,-1,0
  4668.6    0.05       0  5189.4    0.03       0  5193.4    0.05       0
Bank Sta=5189.4,5193.4
Exp/Cntr=0.3,0.1

Type RM Length L Ch R = 1,952,0,0,0
BEGIN DESCRIPTION:
Elm 02 09 952.19
END DESCRIPTION:
XS GIS Cut Line= 5
      1597622.11      6839368.48      1597425.07      6839531.79
      1597418.39      6839843.79      1597451.96      6840090.72
      1597595.48      6840247.44
#Sta/Elev= 30
  4438.3 1730.67  4471.9 1730.00  4499.5 1730.28  4550.0 1729.51  4585.2 1727.72
  4634.6 1726.21  4663.3 1723.27  4700.4 1722.25  4710.4 1721.52  4720.4 1719.48
  4730.4 1717.10  4750.4 1711.13  4760.4 1709.62  4790.5 1709.75  4808.5 1706.30
  4808.7 1705.80  4812.2 1705.80  4812.5 1706.30  5141.7 1706.48  5151.8 1710.08
  5161.8 1712.41  5166.8 1711.39  5192.2 1721.58  5202.3 1722.47  5222.5 1723.38
  5312.3 1724.83  5354.9 1726.08  5390.0 1724.78  5432.6 1724.54  5468.0 1725.64
#Mann=3,-1,0
  4438.3    0.05       0  4808.5    0.03       0  4812.5    0.05       0
Bank Sta=4808.5,4812.5
Exp/Cntr=0.3,0.1

Chan Stop Cuts=-1