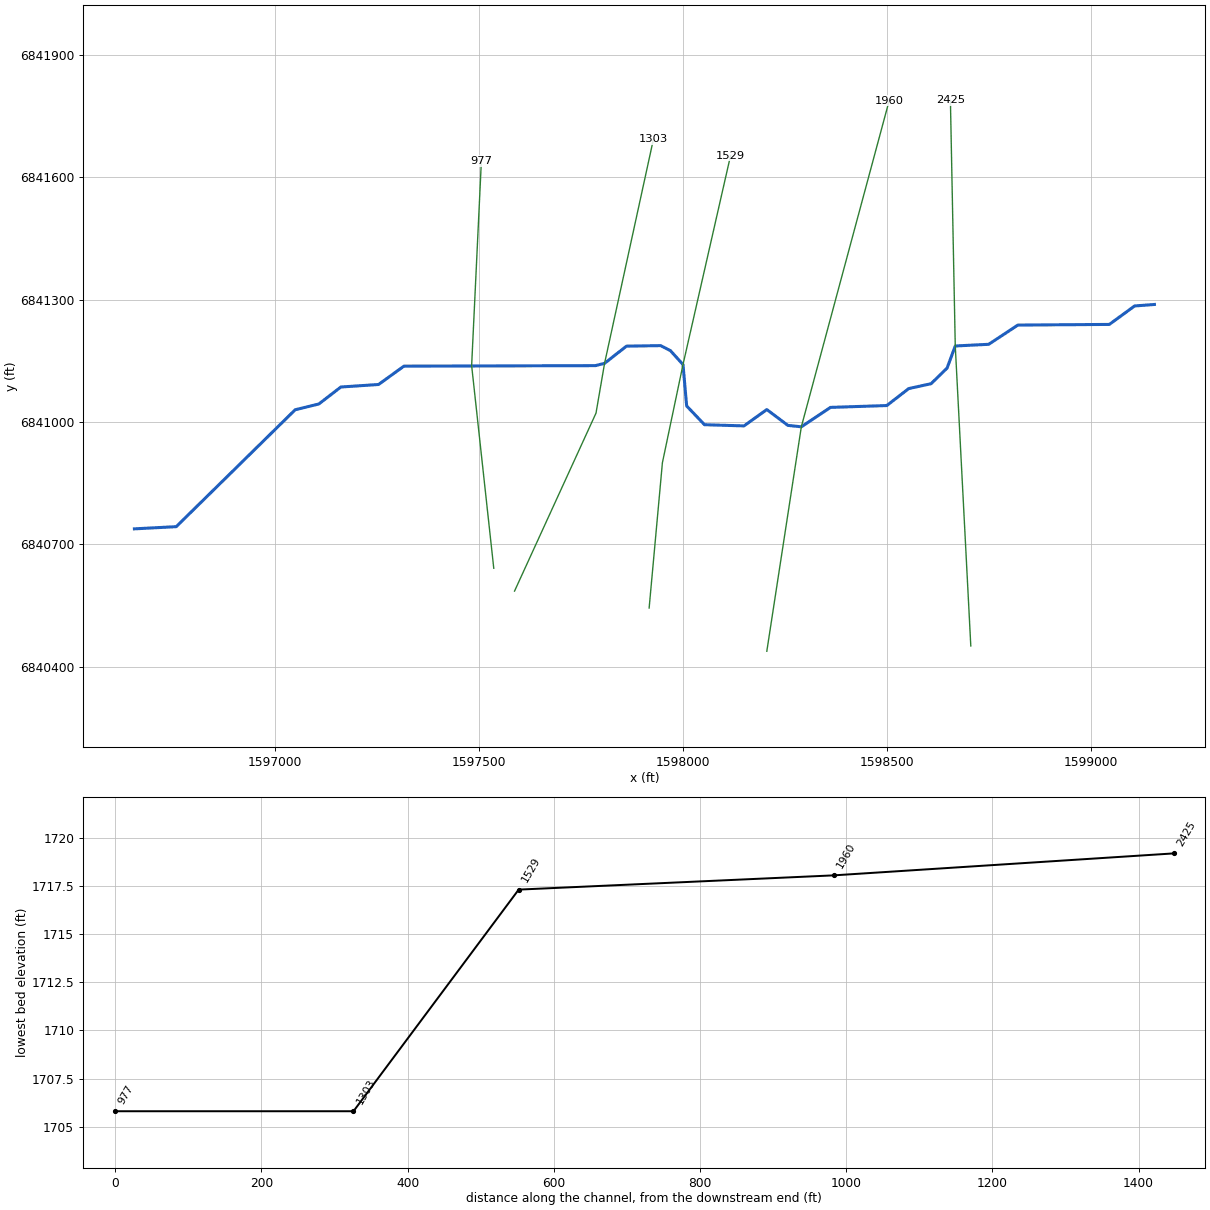
--- Elm 02 10.prj (project) ---

Proj Title=Elm 02 10 Base Level Engineering
Current Plan=p01
Default Exp/Contr=0.3,0.1
English Units
Geom File=g01
Flow File=f01
Plan File=p01
BEGIN DESCRIPTION:
Elm 02 10
END DESCRIPTION:

--- Elm 02 10.p01 (plan) ---

Plan Title=Multiple Run
Short Identifier=Multiple
Geom File=g01
Flow File=f01
Subcritical Flow
K Sum by GR= 0
Std Step Tol= 0.01
Critical Tol= 0.01
Num of Std Step Trials= 20
Max Error Tol= 0.3
Flow Tol Ratio= 0.001
Split Flow NTrial= 30
Split Flow Tol= 0.02
Split Flow Ratio= 0.02
Log Output Level= 0
Friction Slope Method= 1
Unsteady Friction Slope Method= 2
Unsteady Bridges Friction Slope Method= 1
Parabolic Critical Depth
Global Vel Dist=  1 , 1 , 1
Global Log Level= 0
CheckData=True
Encroach Param= -1, 0, 0, 0
BEGIN DESCRIPTION:
Multiple Run
END DESCRIPTION:

--- Elm 02 10.f01 (steady flow) ---

Flow Title=Multiple
Number of Profiles=7
Profile Names=10-year,25-year,50-year,1pct_min,100-year,1pct_plu,500-year
River Rch & RM= Elm 02 10,Reach-1,2425
     112     148     176     130     209     287     297
Boundary for River Rch & Prof#=Elm 02 10,Reach-1,1
Up Type=0
Dn Type=3
Dn Slope=0.001
Boundary for River Rch & Prof#=Elm 02 10,Reach-1,2
Up Type=0
Dn Type=3
Dn Slope=0.001
Boundary for River Rch & Prof#=Elm 02 10,Reach-1,3
Up Type=0
Dn Type=3
Dn Slope=0.001
Boundary for River Rch & Prof#=Elm 02 10,Reach-1,4
Up Type=0
Dn Type=3
Dn Slope=0.001
Boundary for River Rch & Prof#=Elm 02 10,Reach-1,5
Up Type=0
Dn Type=3
Dn Slope=0.001
Boundary for River Rch & Prof#=Elm 02 10,Reach-1,6
Up Type=0
Dn Type=3
Dn Slope=0.001
Boundary for River Rch & Prof#=Elm 02 10,Reach-1,7
Up Type=0
Dn Type=3
Dn Slope=0.001

--- Elm 02 10.g01 (geometry) ---

Geom Title=Existing Conditions

River Reach=Elm 02 10,Reach-1
Reach XY= 30
      1599155.00      6841288.00      1599106.51      6841284.35
      1599044.54      6841239.12      1598820.21      6841237.48
      1598748.94      6841190.39      1598666.88      6841186.24
      1598646.82      6841132.01      1598607.53      6841093.77
      1598552.85      6841081.85      1598499.07      6841040.25
      1598360.93      6841035.70      1598289.58      6840988.15
      1598256.64      6840991.61      1598205.01      6841030.40
      1598149.10      6840990.36      1598052.29      6840993.28
      1598008.52      6841039.25      1597999.59      6841140.71
      1597968.72      6841174.84      1597944.69      6841187.14
      1597860.98      6841185.84      1597807.34      6841143.75
      1597784.97      6841138.07      1597315.50      6841136.78
      1597253.40      6841091.86      1597160.97      6841085.67
      1597107.17      6841044.14      1597048.94      6841029.86
      1596757.50      6840743.35      1596655.00      6840738.00

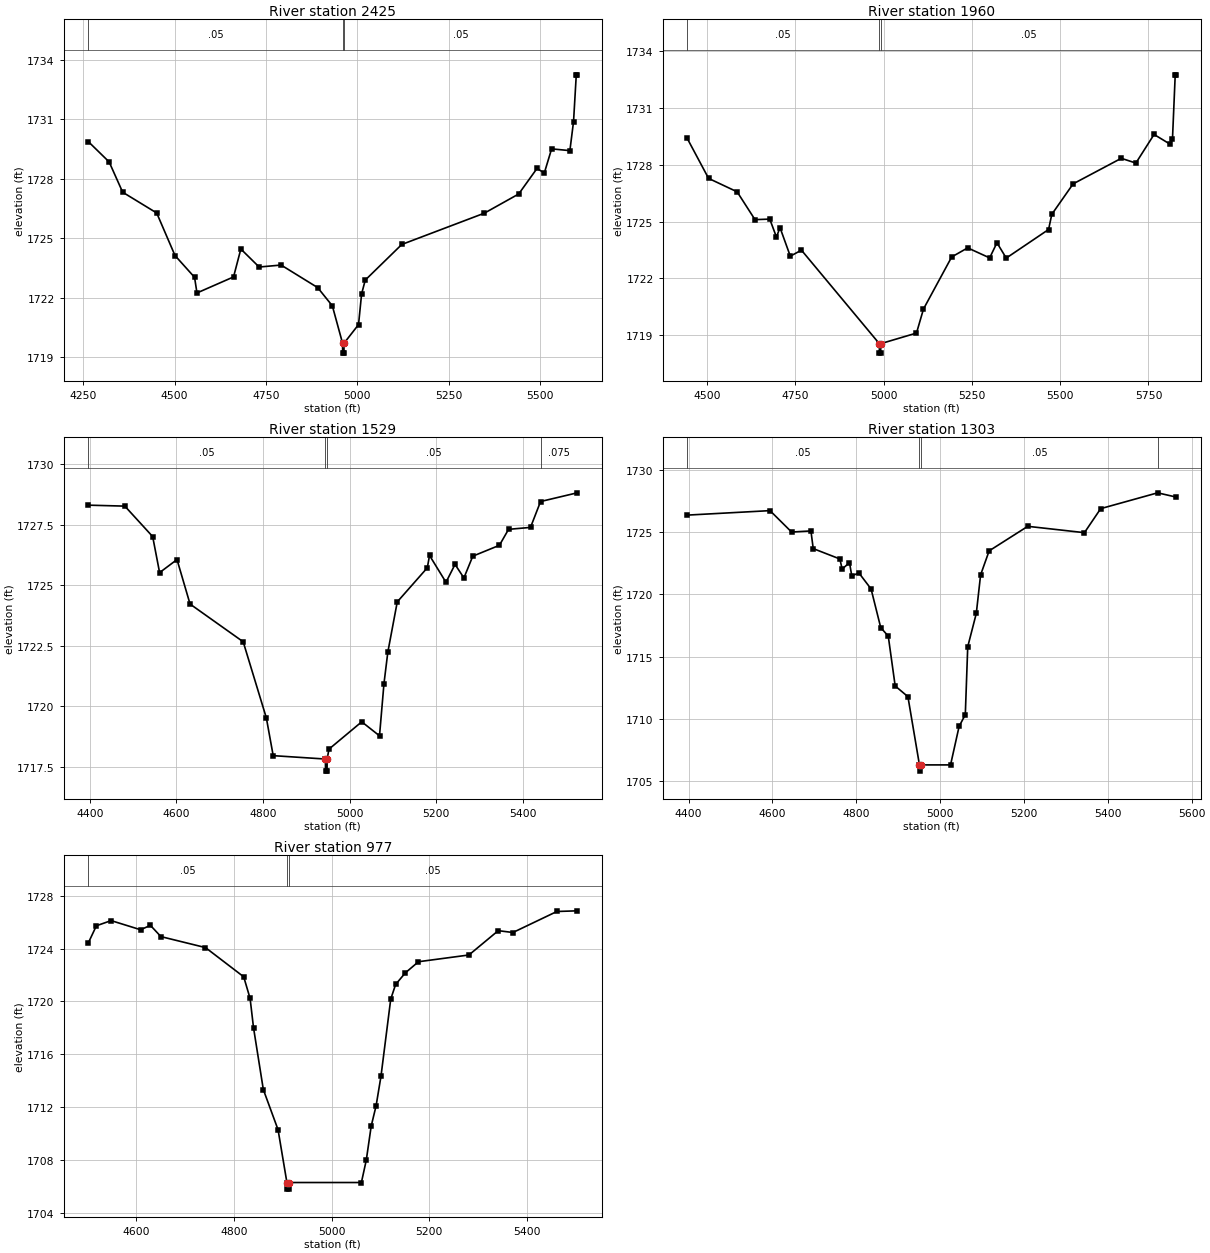
Type RM Length L Ch R = 1,2425,465,465,465
BEGIN DESCRIPTION:
Elm 02 10 2425.067
END DESCRIPTION:
XS GIS Cut Line= 3
      1598704.97      6840450.83      1598666.88      6841186.24
      1598655.00      6841788.03
#Sta/Elev= 30
  4263.6 1729.88  4320.8 1728.85  4357.8 1727.32  4451.0 1726.27  4501.1 1724.12
  4554.6 1723.02  4561.2 1722.23  4661.3 1723.04  4681.3 1724.45  4731.4 1723.54
  4791.5 1723.64  4891.6 1722.50  4931.7 1721.58  4959.7 1719.69  4960.0 1719.19
  4963.5 1719.19  4963.7 1719.69  5003.4 1720.63  5011.8 1722.18  5021.8 1722.88
  5121.8 1724.68  5347.7 1726.26  5441.8 1727.23  5491.9 1728.52  5511.9 1728.29
  5531.9 1729.51  5581.9 1729.42  5591.9 1730.89  5599.4 1733.25  5601.9 1733.25
#Mann=3,-1,0
  4263.6    0.05       0  4959.7    0.05       0  4963.7    0.05       0
Bank Sta=4959.7,4963.7
Exp/Cntr=0.3,0.1

Type RM Length L Ch R = 1,1960,431,431,431
BEGIN DESCRIPTION:
Elm 02 10 1960.164
END DESCRIPTION:
XS GIS Cut Line= 3
      1598205.00      6840438.02      1598289.58      6840988.15
      1598504.99      6841787.95
#Sta/Elev= 30
  4443.4 1729.40  4504.1 1727.28  4585.0 1726.57  4635.6 1725.10  4677.4 1725.13
  4696.3 1724.18  4706.4 1724.68  4735.6 1723.17  4767.1 1723.49  4987.7 1718.55
  4988.0 1718.05  4991.5 1718.05  4991.7 1718.55  5093.0 1719.11  5112.8 1720.38
  5192.7 1723.13  5238.0 1723.61  5300.2 1723.08  5320.9 1723.88  5347.2 1723.07
  5467.1 1724.58  5476.2 1725.38  5536.6 1726.99  5673.0 1728.34  5714.4 1728.09
  5765.9 1729.60  5811.0 1729.09  5818.0 1729.34  5825.8 1732.75  5828.3 1732.75
#Mann=3,-1,0
  4443.4    0.05       0  4987.7    0.03       0  4991.7    0.05       0
Bank Sta=4987.7,4991.7
Exp/Cntr=0.3,0.1

Type RM Length L Ch R = 1,1529,226,226,226
BEGIN DESCRIPTION:
Elm 02 10 1482.772
END DESCRIPTION:
XS GIS Cut Line= 4
      1597916.56      6840543.84      1597949.11      6840900.17
      1597999.59      6841140.71      1598116.19      6841653.12
#Sta/Elev= 30
  4396.4 1728.31  4480.9 1728.27  4545.2 1727.01  4561.2 1725.52  4601.4 1726.06
  4631.5 1724.22  4754.2 1722.66  4807.7 1719.51  4823.5 1717.95  4944.1 1717.81
  4944.4 1717.31  4947.9 1717.31  4948.1 1717.81  4952.3 1718.22  5028.0 1719.35
  5069.0 1718.77  5079.3 1720.93  5088.2 1722.23  5110.0 1724.31  5179.4 1725.72
  5184.5 1726.23  5222.5 1725.12  5243.4 1725.86  5263.9 1725.30  5284.4 1726.20
  5345.9 1726.65  5367.0 1727.31  5417.7 1727.39  5440.9 1728.46  5525.5 1728.82
#Mann=4,-1,0
  4396.4    0.05       0  4944.1    0.03       0  4948.1    0.05       0
  5440.9   0.075       0
Bank Sta=4944.1,4948.1
Exp/Cntr=0.3,0.1

Type RM Length L Ch R = 1,1303,326,326,326
BEGIN DESCRIPTION:
Elm 02 10 998.36
END DESCRIPTION:
XS GIS Cut Line= 4
      1597586.68      6840585.47      1597786.35      6841021.69
      1597807.34      6841143.75      1597927.25      6841693.73
#Sta/Elev= 30
  4396.4 1726.36  4594.1 1726.72  4645.6 1725.00  4691.7 1725.09  4697.2 1723.67
  4760.7 1722.84  4766.2 1722.03  4783.7 1722.54  4789.2 1721.48  4806.1 1721.72
  4835.2 1720.43  4858.2 1717.33  4876.2 1716.64  4892.7 1712.64  4923.1 1711.78
  4950.6 1706.30  4950.9 1705.80  4954.6 1706.30  5024.8 1706.30  5045.3 1709.40
  5060.0 1710.33  5065.8 1715.79  5086.2 1718.46  5096.5 1721.56  5116.9 1723.49
  5209.0 1725.46  5344.2 1724.95  5383.0 1726.88  5518.8 1728.15  5562.9 1727.81
#Mann=4,-1,0
  4396.4    0.05       0  4950.6    0.03       0  4954.6    0.05       0
  5518.8   0.075       0
Bank Sta=4950.6,4954.6
Exp/Cntr=0.3,0.1

Type RM Length L Ch R = 1,977,0,0,0
BEGIN DESCRIPTION:
Elm 02 10 976.7
END DESCRIPTION:
XS GIS Cut Line= 3
      1597535.76      6840641.39      1597481.52      6841138.30
      1597505.38      6841639.57
#Sta/Elev= 30
  4501.2 1724.41  4517.9 1725.72  4548.1 1726.11  4608.4 1725.42  4628.6 1725.75
  4650.1 1724.90  4741.4 1724.07  4819.7 1721.86  4832.8 1720.22  4839.8 1718.01
  4859.9 1713.33  4890.1 1710.29  4908.2 1706.30  4908.5 1705.80  4912.0 1705.80
  4912.2 1706.30  5060.8 1706.30  5070.8 1707.99  5080.9 1710.57  5090.9 1712.10
  5100.9 1714.33  5120.9 1720.17  5130.9 1721.28  5150.9 1722.16  5177.7 1723.00
  5281.1 1723.51  5341.2 1725.35  5371.2 1725.21  5461.3 1726.80  5502.9 1726.85
#Mann=3,-1,0
  4501.2    0.05       0  4908.2    0.03       0  4912.2    0.05       0
Bank Sta=4908.2,4912.2
Exp/Cntr=0.3,0.1

Chan Stop Cuts=-1