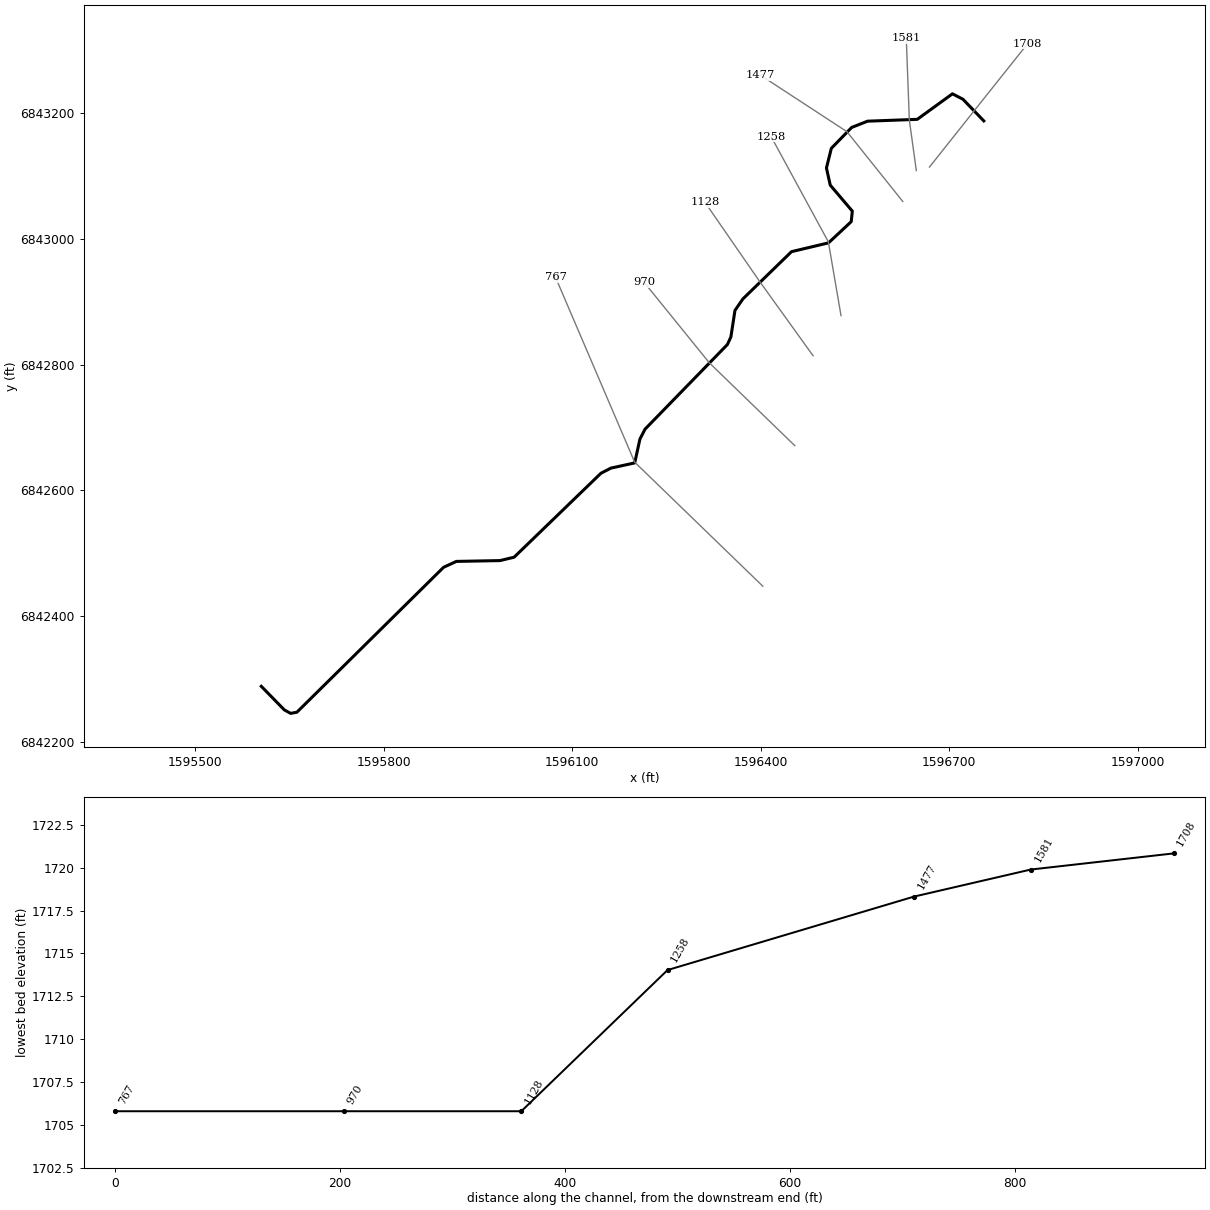
--- Elm 02 11.prj (project) ---

Proj Title=Elm 02 11 Base Level Engineering
Current Plan=p01
Default Exp/Contr=0.3,0.1
English Units
Geom File=g01
Flow File=f01
Plan File=p01
BEGIN DESCRIPTION:
Elm 02 11
END DESCRIPTION:

--- Elm 02 11.p01 (plan) ---

Plan Title=Multiple Run
Short Identifier=Multiple
Geom File=g01
Flow File=f01
Subcritical Flow
K Sum by GR= 0
Std Step Tol= 0.01
Critical Tol= 0.01
Num of Std Step Trials= 20
Max Error Tol= 0.3
Flow Tol Ratio= 0.001
Split Flow NTrial= 30
Split Flow Tol= 0.02
Split Flow Ratio= 0.02
Log Output Level= 0
Friction Slope Method= 1
Unsteady Friction Slope Method= 2
Unsteady Bridges Friction Slope Method= 1
Parabolic Critical Depth
Global Vel Dist=  1 , 1 , 1
Global Log Level= 0
CheckData=True
Encroach Param= -1, 0, 0, 0
BEGIN DESCRIPTION:
Multiple Run
END DESCRIPTION:

--- Elm 02 11.f01 (steady flow) ---

Flow Title=Multiple
Number of Profiles=7
Profile Names=10-year,25-year,50-year,1pct_min,100-year,1pct_plu,500-year
River Rch & RM= Elm 02 11,Reach-1,1708
      34      41      47      33      52      72      67
Boundary for River Rch & Prof#=Elm 02 11,Reach-1,1
Up Type=0
Dn Type=3
Dn Slope=0.001
Boundary for River Rch & Prof#=Elm 02 11,Reach-1,2
Up Type=0
Dn Type=3
Dn Slope=0.001
Boundary for River Rch & Prof#=Elm 02 11,Reach-1,3
Up Type=0
Dn Type=3
Dn Slope=0.001
Boundary for River Rch & Prof#=Elm 02 11,Reach-1,4
Up Type=0
Dn Type=3
Dn Slope=0.001
Boundary for River Rch & Prof#=Elm 02 11,Reach-1,5
Up Type=0
Dn Type=3
Dn Slope=0.001
Boundary for River Rch & Prof#=Elm 02 11,Reach-1,6
Up Type=0
Dn Type=3
Dn Slope=0.001
Boundary for River Rch & Prof#=Elm 02 11,Reach-1,7
Up Type=0
Dn Type=3
Dn Slope=0.001

--- Elm 02 11.g01 (geometry) ---

Geom Title=Existing Conditions

River Reach=Elm 02 11,Reach-1
Reach XY= 30
      1596755.00      6843188.00      1596721.84      6843222.46
      1596705.14      6843231.10      1596649.12      6843190.47
      1596570.06      6843187.54      1596544.78      6843177.62
      1596512.37      6843144.37      1596504.56      6843113.09
      1596510.63      6843085.72      1596545.73      6843044.40
      1596544.02      6843027.63      1596507.84      6842993.85
      1596448.98      6842979.85      1596371.64      6842904.71
      1596358.97      6842886.36      1596352.46      6842844.05
      1596346.84      6842831.95      1596215.89      6842697.42
      1596207.69      6842681.57      1596199.38      6842643.62
      1596161.43      6842635.31      1596145.58      6842627.11
      1596007.43      6842493.52      1595984.94      6842488.13
      1595915.48      6842486.83      1595895.21      6842477.48
      1595661.67      6842246.77      1595651.67      6842244.94
      1595641.67      6842250.50      1595605.00      6842288.00

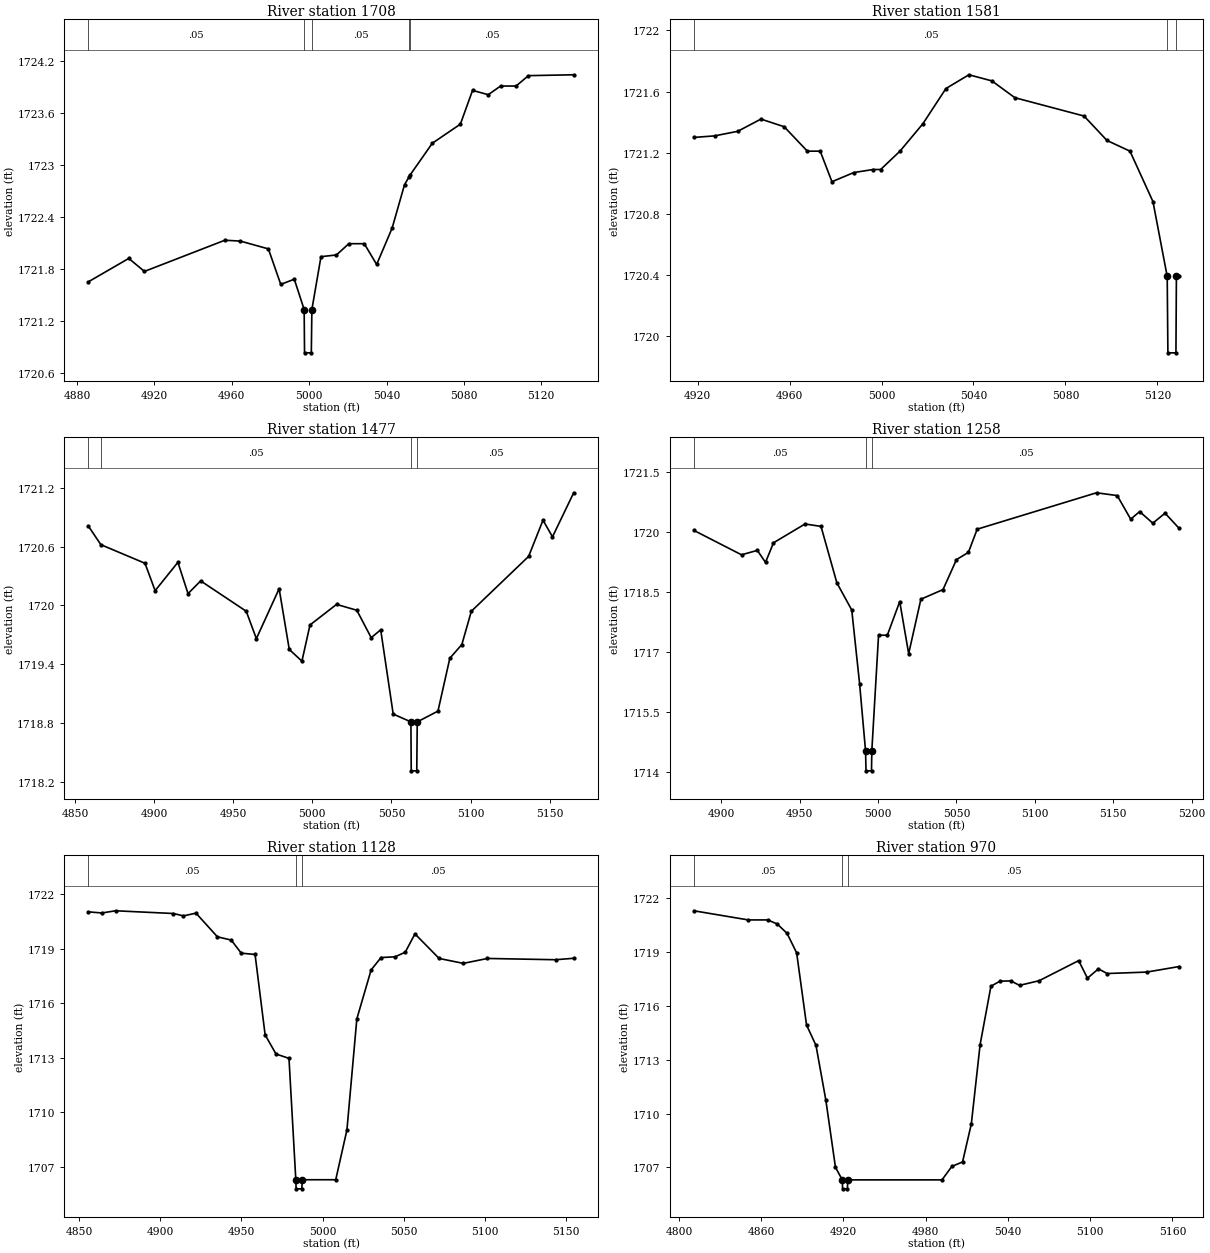
Type RM Length L Ch R = 1,1708,127,127,127
BEGIN DESCRIPTION:
Elm 02 11 1024.571
END DESCRIPTION:
XS GIS Cut Line= 3
      1596668.59      6843114.56      1596739.60      6843204.00
      1596824.86      6843310.98
#Sta/Elev= 29
  4885.8 1721.65  4906.7 1721.92  4914.8 1721.77  4956.4 1722.13  4964.4 1722.12
  4978.9 1722.03  4985.3 1721.62  4992.3 1721.68  4997.4 1721.33  4997.6 1720.83
  5001.1 1720.83  5001.4 1721.33  5006.1 1721.94  5014.1 1721.96  5020.5 1722.09
  5028.5 1722.09  5034.9 1721.85  5042.9 1722.27  5049.3 1722.77  5051.6 1722.86
  5052.1 1722.88  5063.7 1723.25  5078.2 1723.47  5084.5 1723.86  5092.6 1723.81
  5099.0 1723.91  5107.0 1723.91  5113.4 1724.03  5136.8 1724.04
#Mann=5,-1,0
  4885.8    0.05       0  4997.4    0.05       0  5001.4    0.05       0
  5051.6   0.075       0  5052.1    0.05       0
Bank Sta=4997.4,5001.4
Exp/Cntr=0.3,0.1

Type RM Length L Ch R = 1,1581,104,104,104
BEGIN DESCRIPTION:
Elm 02 11 1581.13
END DESCRIPTION:
XS GIS Cut Line= 3
      1596647.60      6843109.06      1596636.49      6843189.58
      1596631.63      6843319.41
#Sta/Elev= 26
  4918.3 1721.30  4927.3 1721.31  4937.4 1721.34  4947.5 1721.42  4957.6 1721.37
  4967.7 1721.21  4973.3 1721.21  4978.4 1721.01  4987.9 1721.07  4996.3 1721.09
  4999.6 1721.09  5008.0 1721.21  5018.0 1721.39  5028.0 1721.62  5038.0 1721.71
  5048.0 1721.67  5058.0 1721.56  5088.1 1721.44  5098.1 1721.28  5108.1 1721.21
  5118.1 1720.88  5124.3 1720.39  5124.6 1719.89  5128.1 1719.89  5128.3 1720.39
  5129.5 1720.39
#Mann=3,-1,0
  4918.3    0.05       0  5124.3    0.05       0  5128.3    0.05       0
Bank Sta=5124.3,5128.3
Exp/Cntr=0.3,0.1

Type RM Length L Ch R = 1,1477,219,219,219
BEGIN DESCRIPTION:
Elm 02 11 1476.9
END DESCRIPTION:
XS GIS Cut Line= 3
      1596626.08      6843059.71      1596537.19      6843170.83
      1596399.47      6843260.79
#Sta/Elev= 30
  4858.4 1720.81  4866.3 1720.62  4894.2 1720.43  4900.6 1720.15  4915.0 1720.44
  4921.4 1720.12  4929.4 1720.25  4958.2 1719.94  4964.6 1719.66  4979.0 1720.17
  4985.4 1719.55  4993.4 1719.43  4998.5 1719.80  5015.3 1720.01  5028.1 1719.95
  5037.2 1719.67  5043.2 1719.75  5051.1 1718.89  5062.3 1718.81  5062.5 1718.31
  5066.0 1718.31  5066.3 1718.81  5079.4 1718.92  5086.9 1719.46  5094.5 1719.60
  5100.5 1719.94  5136.7 1720.50  5145.8 1720.87  5151.8 1720.70  5165.2 1721.15
#Mann=4,-1,0
  4858.4   0.075       0  4866.3    0.05       0  5062.3    0.05       0
  5066.3    0.05       0
Bank Sta=5062.3,5066.3
Exp/Cntr=0.3,0.1

Type RM Length L Ch R = 1,1258,130,130,130
BEGIN DESCRIPTION:
Elm 02 11 1258.41
END DESCRIPTION:
XS GIS Cut Line= 3
      1596527.76      6842878.08      1596507.63      6842995.40
      1596416.67      6843162.74
#Sta/Elev= 30
  4882.5 1720.04  4912.9 1719.43  4923.0 1719.54  4928.2 1719.24  4933.3 1719.73
  4953.4 1720.20  4963.6 1720.14  4973.7 1718.73  4983.2 1718.05  4988.2 1716.21
  4992.0 1714.53  4992.3 1714.03  4995.8 1714.03  4996.0 1714.53  5000.3 1717.42
  5005.9 1717.42  5013.8 1718.26  5019.5 1716.96  5027.3 1718.32  5041.4 1718.56
  5050.0 1719.31  5057.6 1719.49  5063.2 1720.07  5139.3 1720.98  5152.5 1720.91
  5161.1 1720.32  5166.8 1720.51  5175.2 1720.22  5183.0 1720.47  5192.0 1720.09
#Mann=3,-1,0
  4882.5    0.05       0  4992.0    0.03       0  4996.0    0.05       0
Bank Sta=4992,4996
Exp/Cntr=0.3,0.1

Type RM Length L Ch R = 1,1128,158,158,158
BEGIN DESCRIPTION:
Elm 02 11 1127.87
END DESCRIPTION:
XS GIS Cut Line= 3
      1596483.30      6842814.18      1596397.91      6842932.90
      1596311.10      6843058.60
#Sta/Elev= 30
  4855.7 1721.02  4864.0 1720.96  4872.5 1721.08  4908.1 1720.93  4914.3 1720.80
  4922.0 1720.95  4935.2 1719.65  4943.7 1719.47  4949.9 1718.75  4958.4 1718.68
  4964.6 1714.26  4971.3 1713.21  4979.3 1712.97  4983.5 1706.30  4983.7 1705.80
  4987.2 1705.80  4987.5 1706.30  5008.1 1706.30  5015.0 1709.04  5021.1 1715.14
  5029.9 1717.83  5036.0 1718.51  5044.6 1718.55  5050.9 1718.80  5056.9 1719.81
  5071.8 1718.46  5086.7 1718.19  5101.6 1718.46  5143.5 1718.39  5154.7 1718.47
#Mann=3,-1,0
  4855.7    0.05       0  4983.5    0.03       0  4987.5    0.05       0
Bank Sta=4983.5,4987.5
Exp/Cntr=0.3,0.1

Type RM Length L Ch R = 1,970,203,203,203
BEGIN DESCRIPTION:
Elm 02 11 970.42
END DESCRIPTION:
XS GIS Cut Line= 3
      1596454.15      6842671.09      1596318.05      6842803.04
      1596214.56      6842930.83
#Sta/Elev= 30
  4810.9 1721.31  4850.6 1720.80  4864.8 1720.80  4871.8 1720.57  4878.9 1720.05
  4885.9 1718.96  4893.1 1714.94  4900.0 1713.80  4907.2 1710.74  4914.2 1707.00
  4919.2 1706.30  4919.4 1705.80  4922.9 1705.80  4923.2 1706.30  4991.9 1706.30
  4999.1 1707.05  5006.9 1707.30  5013.3 1709.42  5019.7 1713.84  5027.6 1717.10
  5034.1 1717.38  5042.0 1717.40  5048.5 1717.15  5062.8 1717.41  5091.6 1718.53
  5098.0 1717.55  5106.0 1718.07  5112.4 1717.81  5141.2 1717.89  5164.9 1718.20
#Mann=3,-1,0
  4810.9    0.05       0  4919.2    0.05       0  4923.2    0.05       0
Bank Sta=4919.2,4923.2
Exp/Cntr=0.3,0.1

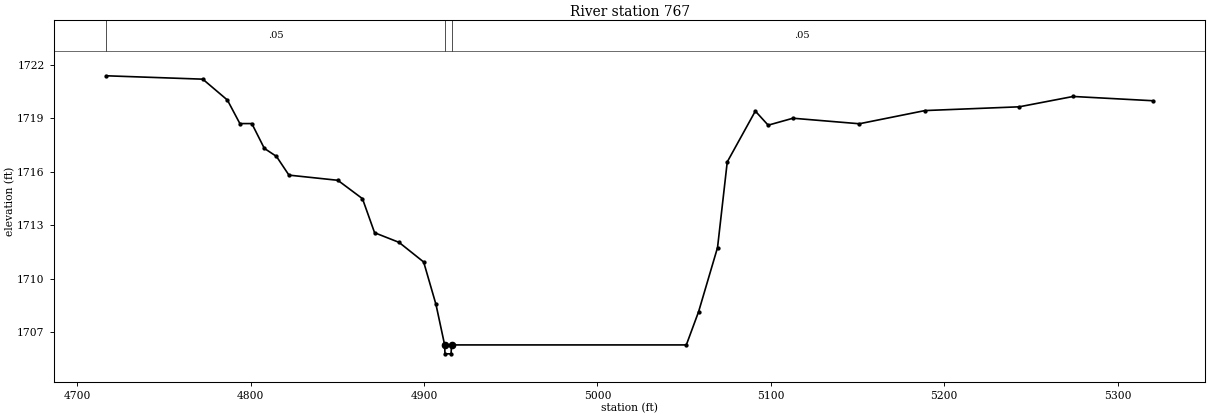
Type RM Length L Ch R = 1,767,0,0,0
BEGIN DESCRIPTION:
Elm 02 11 767.38
END DESCRIPTION:
XS GIS Cut Line= 3
      1596403.27      6842447.37      1596199.30      6842644.83
      1596073.41      6842938.93
#Sta/Elev= 30
  4716.7 1721.39  4772.4 1721.20  4786.6 1720.03  4793.8 1718.71  4800.7 1718.71
  4807.9 1717.32  4814.9 1716.87  4822.1 1715.82  4850.3 1715.53  4864.5 1714.50
  4871.5 1712.59  4885.6 1712.05  4899.8 1710.95  4906.9 1708.57  4911.9 1706.30
  4912.1 1705.80  4915.6 1705.80  4915.9 1706.30  5051.3 1706.30  5058.4 1708.17
  5069.3 1711.76  5074.9 1716.56  5091.1 1719.41  5098.5 1718.62  5112.8 1719.01
  5151.1 1718.70  5189.0 1719.44  5243.3 1719.65  5274.4 1720.23  5320.5 1719.99
#Mann=3,-1,0
  4716.7    0.05       0  4911.9    0.03       0  4915.9    0.05       0
Bank Sta=4911.9,4915.9
Exp/Cntr=0.3,0.1

Chan Stop Cuts=-1