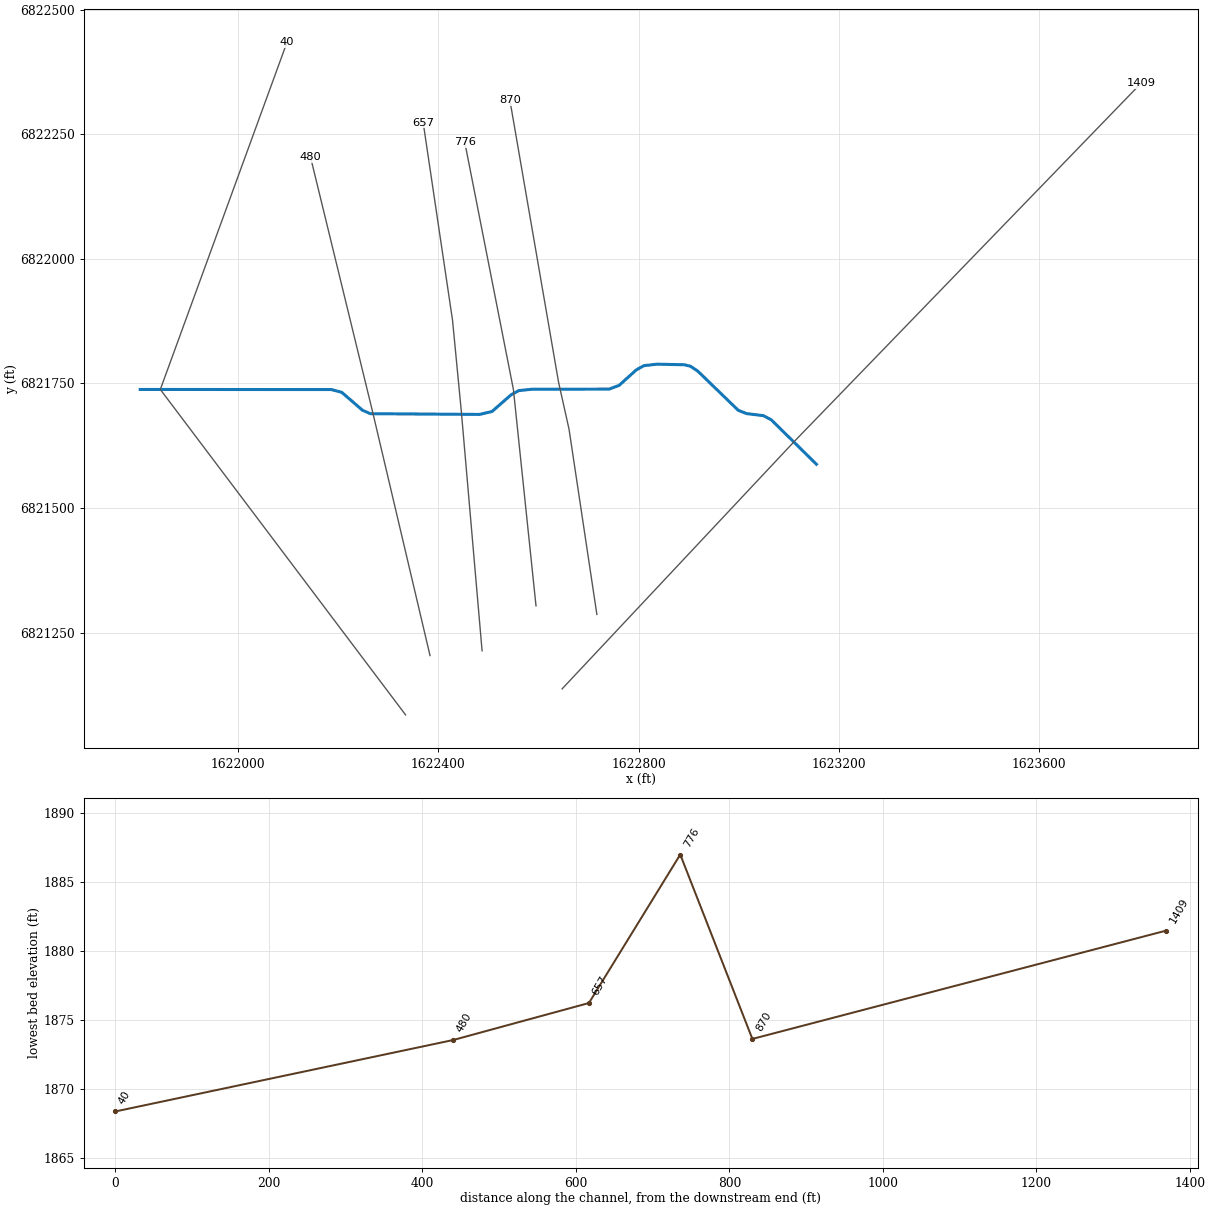
--- Elm 02 14.prj (project) ---

Proj Title=Elm 02 14 Base Level Engineering
Current Plan=p01
Default Exp/Contr=0.3,0.1
English Units
Geom File=g01
Flow File=f01
Plan File=p01
Y Axis Title=Elevation
X Axis Title(PF)=Main Channel Distance
X Axis Title(XS)=Station
BEGIN DESCRIPTION:
Elm 02 14
END DESCRIPTION:
DSS Export Rating Curves= 0
DSS Export Rating Curve Sorted= 0
DSS Export Volume Flow Curves= 0
DXF OffsetX= 0
DXF OffsetY= 0
DXF ScaleX= 1
DXF ScaleY= 10

--- Elm 02 14.p01 (plan) ---

Plan Title=Multiple Run
Short Identifier=Multiple
Geom File=g01
Flow File=f01
Subcritical Flow
K Sum by GR= 0
Std Step Tol= 0.01
Critical Tol= 0.01
Num of Std Step Trials= 20
Max Error Tol= 0.3
Flow Tol Ratio= 0.001
Split Flow NTrial= 30
Split Flow Tol= 0.02
Split Flow Ratio= 0.02
Log Output Level= 0
Friction Slope Method= 1
Unsteady Friction Slope Method= 2
Unsteady Bridges Friction Slope Method= 1
Parabolic Critical Depth
Global Vel Dist=  1 , 1 , 1
Global Log Level= 0
CheckData=True
Encroach Param= -1, 0, 0, 0
BEGIN DESCRIPTION:
Multiple Run
END DESCRIPTION:

--- Elm 02 14.f01 (steady flow) ---

Flow Title=Multiple
Number of Profiles=7
Profile Names=10-year,25-year,50-year,1pct_min,100-year,1pct_plu,500-year
River Rch & RM= Elm 02 14,Reach-1,1409
     211     290     354     269     430     592     644
River Rch & RM= Elm 02 14,Reach-1,40
     541     773     970     753    1210    1660    1890
Boundary for River Rch & Prof#=Elm 02 14,Reach-1,1
Up Type=0
Dn Type=3
Dn Slope=0.001
Boundary for River Rch & Prof#=Elm 02 14,Reach-1,2
Up Type=0
Dn Type=3
Dn Slope=0.001
Boundary for River Rch & Prof#=Elm 02 14,Reach-1,3
Up Type=0
Dn Type=3
Dn Slope=0.001
Boundary for River Rch & Prof#=Elm 02 14,Reach-1,4
Up Type=0
Dn Type=3
Dn Slope=0.001
Boundary for River Rch & Prof#=Elm 02 14,Reach-1,5
Up Type=0
Dn Type=3
Dn Slope=0.001
Boundary for River Rch & Prof#=Elm 02 14,Reach-1,6
Up Type=0
Dn Type=3
Dn Slope=0.001
Boundary for River Rch & Prof#=Elm 02 14,Reach-1,7
Up Type=0
Dn Type=3
Dn Slope=0.001

--- Elm 02 14.g01 (geometry) ---

Geom Title=Existing Conditions
Program Version=4.10

River Reach=Elm 02 14       ,Reach-1
Reach XY= 30
        1623155.        6821588.      1623109.85      6821632.64
       1623064.7      6821677.28      1623048.96      6821685.48
      1623015.64      6821689.54      1622998.96      6821696.17
      1622958.62       6821735.4      1622918.29      6821774.64
       1622903.5      6821784.53      1622891.08      6821787.59
      1622836.77      6821788.66      1622810.57      6821785.72
      1622795.37      6821777.19      1622761.06      6821746.15
      1622741.08      6821738.69      1622663.87      6821738.54
      1622586.66      6821738.39      1622560.53      6821735.62
      1622545.35      6821727.15      1622507.33      6821693.75
      1622482.31      6821687.91      1622409.76       6821688.4
      1622337.21      6821688.89      1622264.66      6821689.38
      1622248.94      6821696.14      1622207.33      6821732.25
      1622186.73      6821737.79      1621995.87      6821737.89
      1621900.43      6821737.95        1621805.        6821738.

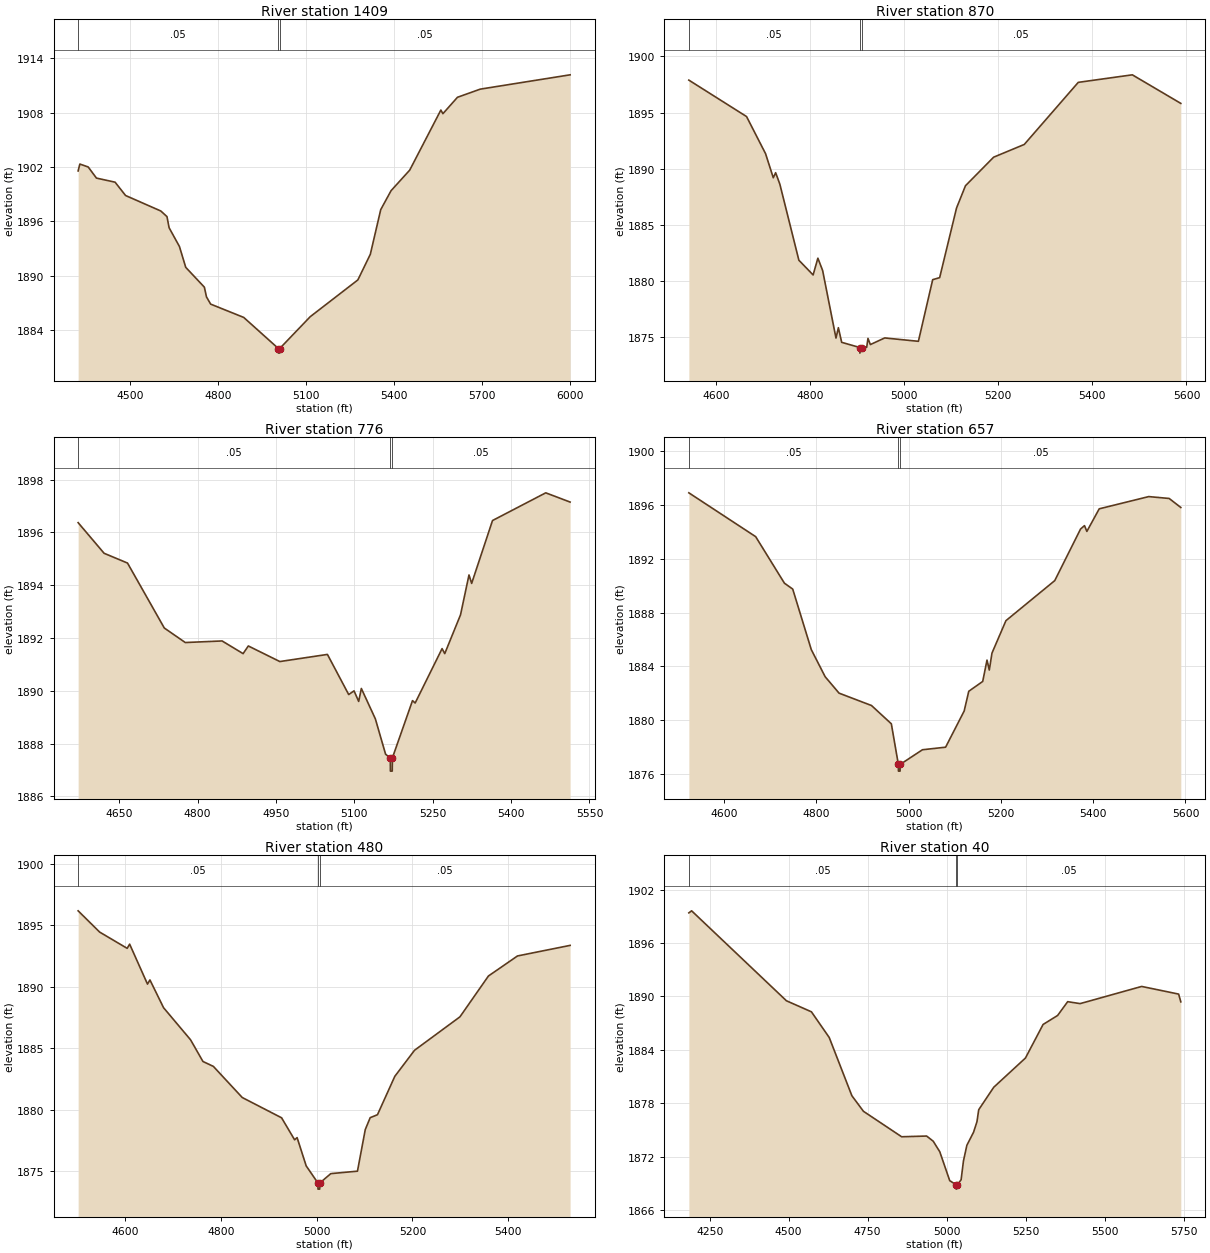
Type RM Length L Ch R = 1 ,1409    ,539,539,539
BEGIN DESCRIPTION:
Elm 02 14 1034.901
END DESCRIPTION:
XS GIS Cut Line= 3
      1622647.27      6821137.37      1623109.85      6821632.64
      1623803.53      6822352.65
#Sta/Elev= 30
  4322.3 1901.56  4328.2 1902.32  4356.5    1902  4384.8 1900.77  4448.3 1900.32
    4484 1898.85  4604.2 1897.14  4625.2 1896.52  4632.5 1895.29  4667.7 1893.22
  4689.2 1890.92  4752.7 1888.73    4760 1887.65  4774.2 1886.86    4887 1885.39
  5005.4 1881.95  5005.7 1881.45  5009.2 1881.45  5009.4 1881.95  5113.6 1885.47
  5276.1 1889.53  5318.6 1892.36  5354.1 1897.29  5389.3 1899.38  5452.9 1901.65
  5559.1 1908.28  5566.1 1907.88  5615.7 1909.69  5693.4 1910.59  5999.8 1912.17
#Mann= 3 ,-1 , 0
  4322.3     .05       0  5005.4     .05       0  5009.4     .05       0
Bank Sta=5005.4,5009.4
XS Rating Curve= 0 ,0
Exp/Cntr=0.3,0.1

Type RM Length L Ch R = 1 ,870     ,94,94,94
BEGIN DESCRIPTION:
Elm 02 14 869.54
END DESCRIPTION:
XS GIS Cut Line= 4
      1622716.71      6821286.69      1622661.16       6821658.2
      1622640.33      6821751.95      1622543.11      6822317.88
#Sta/Elev= 30
  4542.1 1897.88  4664.8 1894.64  4705.2 1891.34  4721.6  1889.2  4726.6 1889.65
  4735.5 1888.64    4776 1881.87  4806.3 1880.56  4816.4 1882.05  4826.5 1880.96
  4854.9 1874.95    4860 1875.87    4867 1874.57  4905.4 1874.11  4905.7 1873.61
  4909.4 1874.11  4920.2 1874.13  4922.9 1874.92    4928 1874.37  4958.5 1874.96
  5030.1 1874.66  5060.5 1880.14  5075.3 1880.32  5111.2 1886.51  5130.2 1888.49
  5190.1 1891.03  5255.2 1892.16    5370 1897.68  5484.9 1898.35    5588 1895.81
#Mann= 3 ,-1 , 0
  4542.1     .05       0  4905.4     .05       0  4909.4     .05       0
Bank Sta=4905.4,4909.4
XS Rating Curve= 0 ,0
Exp/Cntr=0.3,0.1

Type RM Length L Ch R = 1 ,776     ,119,119,119
BEGIN DESCRIPTION:
Elm 02 14 775.54
END DESCRIPTION:
XS GIS Cut Line= 3
      1622595.19      6821304.02      1622550.05      6821738.06
      1622452.99      6822233.77
#Sta/Elev= 30
  4571.5 1896.37  4621.2 1895.21    4666 1894.84  4736.4 1892.38  4776.6 1891.83
    4847 1891.89  4887.2 1891.41  4897.2  1891.7  4957.5 1891.11  5048.6 1891.38
  5089.3 1889.86  5099.5    1890  5108.4  1889.6  5113.5 1890.09  5140.3 1888.94
  5159.9  1887.6  5168.9 1887.46  5169.1 1886.96  5172.6 1886.96  5172.9 1887.46
  5211.4 1889.63  5216.5 1889.54    5268  1891.6  5273.1 1891.41  5303.3 1892.88
  5319.5 1894.39  5324.6 1894.07  5364.5 1896.45  5466.4  1897.5    5513 1897.15
#Mann= 3 ,-1 , 0
  4571.5     .05       0  5168.9     .05       0  5172.9     .05       0
Bank Sta=5168.9,5172.9
XS Rating Curve= 0 ,0
Exp/Cntr=0.3,0.1

Type RM Length L Ch R = 1 ,657     ,177,177,177
BEGIN DESCRIPTION:
Elm 02 14 657.21
END DESCRIPTION:
XS GIS Cut Line= 4
      1622487.55      6821213.71      1622445.88      6821696.39
      1622428.52      6821876.95      1622369.99      6822272.88
#Sta/Elev= 30
  4523.8 1896.91  4668.6 1893.65  4730.9 1890.19  4748.9 1889.75  4789.1 1885.25
  4819.2 1883.23  4849.3 1882.01  4919.6 1881.09  4962.6 1879.73  4977.8 1876.71
    4978 1876.21  4981.5 1876.21  4981.8 1876.71    5030  1877.8  5080.2 1877.99
  5120.4 1880.68  5130.4 1882.15  5160.6 1882.88  5169.9 1884.47  5174.9 1883.73
  5180.7 1884.99  5210.9  1887.4  5316.7 1890.38  5372.7 1894.22  5381.2 1894.47
  5386.3 1894.04  5413.1 1895.72  5520.4 1896.63  5564.7 1896.49  5589.9 1895.82
#Mann= 3 ,-1 , 0
  4523.8     .05       0  4977.8     .03       0  4981.8     .05       0
Bank Sta=4977.8,4981.8
XS Rating Curve= 0 ,0
Exp/Cntr=0.3,0.1

Type RM Length L Ch R = 1 ,480     ,440,440,440
BEGIN DESCRIPTION:
Elm 02 14 480.45
END DESCRIPTION:
XS GIS Cut Line= 3
      1622383.61      6821204.21       1622268.6      6821694.64
      1622145.09      6822203.84
#Sta/Elev= 30
  4501.7 1896.16  4546.7 1894.43  4604.1 1893.11  4609.3 1893.45  4646.6  1890.2
  4651.7 1890.54  4680.2 1888.28  4736.6 1885.67  4762.4 1883.91  4784.2 1883.51
  4844.5 1880.98  4926.7 1879.33  4953.9 1877.54  4959.1 1877.72  4978.1 1875.42
  5002.6 1874.03  5002.8 1873.53  5006.3 1873.53  5006.6 1874.03  5029.5 1874.79
  5085.2 1874.99  5101.5 1878.37  5111.8 1879.34    5127 1879.58  5163.2  1882.7
  5204.4 1884.82  5299.3 1887.54  5358.8 1890.86  5419.5 1892.49  5529.4 1893.35
#Mann= 3 ,-1 , 0
  4501.7     .05       0  5002.6     .04       0  5006.6     .05       0
Bank Sta=5002.6,5006.6
XS Rating Curve= 0 ,0
Exp/Cntr=0.3,0.1

Type RM Length L Ch R = 1 ,40      ,0,0,0
BEGIN DESCRIPTION:
Elm 02 14 547.822
END DESCRIPTION:
XS GIS Cut Line= 3
      1622334.77      6821085.29      1621845.18      6821737.98
      1622098.11      6822434.47
#Sta/Elev= 30
  4184.1 1899.38  4192.9 1899.61  4492.9 1889.51    4572 1888.27  4628.3 1885.39
    4700 1878.85  4736.6  1877.1  4857.5 1874.24  4936.6 1874.32  4957.5 1873.74
  4978.3 1872.55  5009.7 1869.31  5029.9 1868.86  5030.2 1868.36  5033.9 1868.86
  5045.7 1869.41  5053.2 1871.54  5063.9 1873.28  5085.1 1874.75  5095.8 1875.92
  5101.5 1877.28    5149  1879.8  5249.3 1883.08  5305.2 1886.85  5351.1 1887.86
    5383 1889.41  5422.3 1889.19  5617.1 1891.12  5734.1 1890.26    5741 1889.39
#Mann= 3 ,-1 , 0
  4184.1     .05       0  5029.9     .05       0  5033.9     .05       0
Bank Sta=5029.9,5033.9
XS Rating Curve= 0 ,0
Exp/Cntr=0.3,0.1

Chan Stop Cuts=-1
Use User Specified Reach Order=0
Composite Channel Slope=5