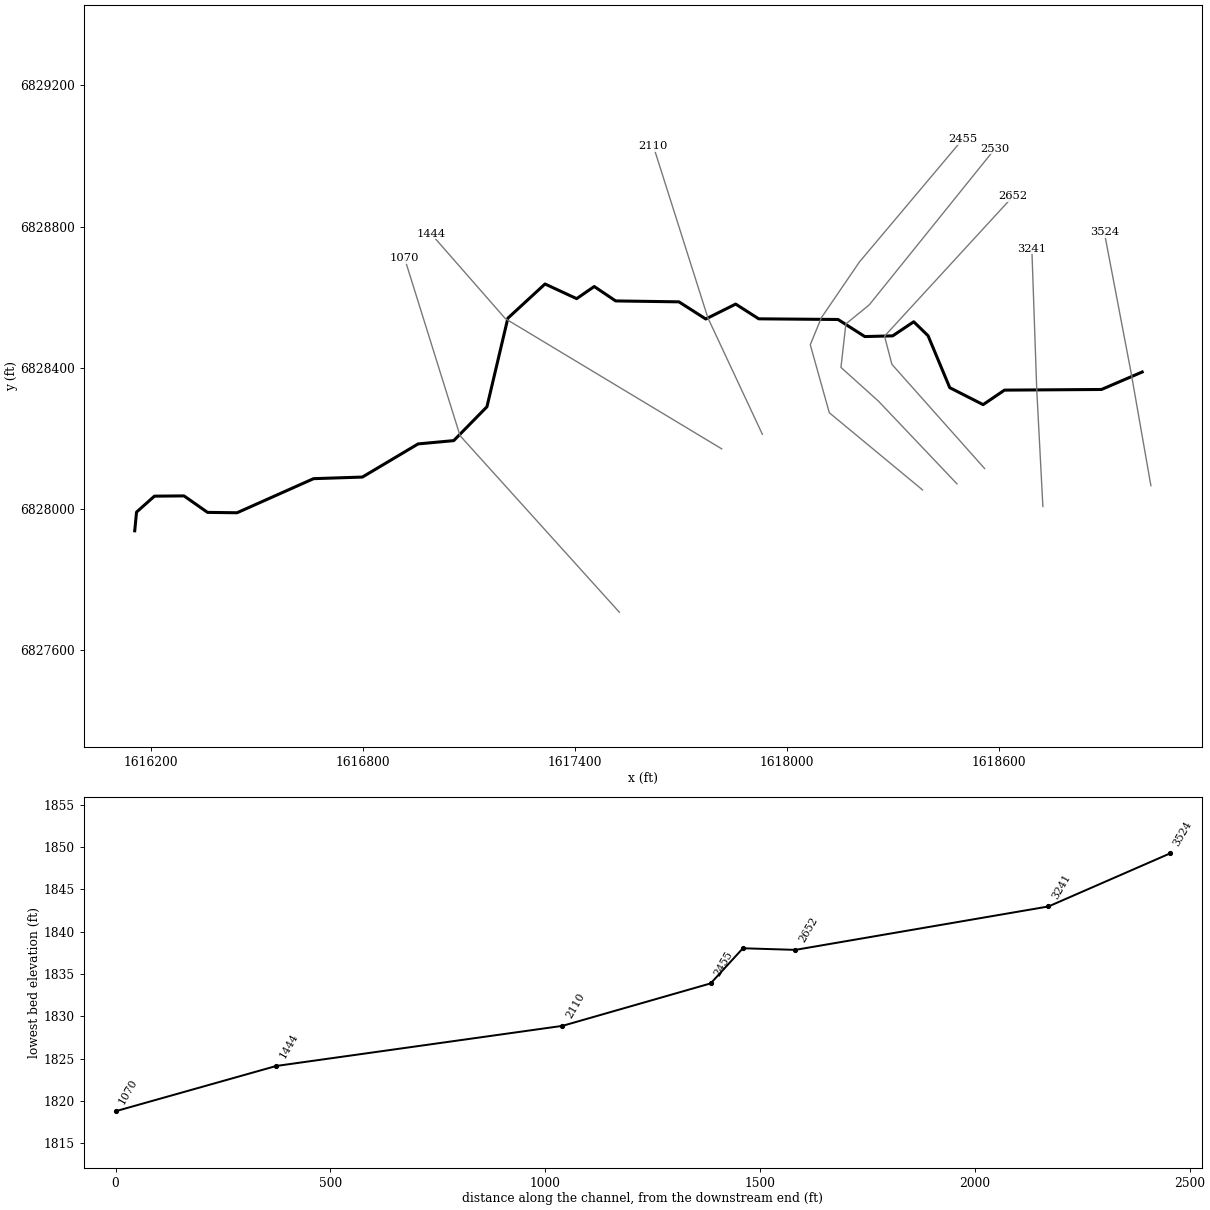
--- Elm 02 15.prj (project) ---

Proj Title=Elm 02 15 Base Level Engineering
Current Plan=p01
Default Exp/Contr=0.3,0.1
English Units
Geom File=g01
Flow File=f01
Plan File=p01
BEGIN DESCRIPTION:
Elm 02 15
END DESCRIPTION:

--- Elm 02 15.p01 (plan) ---

Plan Title=Multiple Run
Short Identifier=Multiple
Geom File=g01
Flow File=f01
Subcritical Flow
K Sum by GR= 0
Std Step Tol= 0.01
Critical Tol= 0.01
Num of Std Step Trials= 20
Max Error Tol= 0.3
Flow Tol Ratio= 0.001
Split Flow NTrial= 30
Split Flow Tol= 0.02
Split Flow Ratio= 0.02
Log Output Level= 0
Friction Slope Method= 1
Unsteady Friction Slope Method= 2
Unsteady Bridges Friction Slope Method= 1
Parabolic Critical Depth
Global Vel Dist=  1 , 1 , 1
Global Log Level= 0
CheckData=True
Encroach Param= -1, 0, 0, 0
BEGIN DESCRIPTION:
Multiple Run
END DESCRIPTION:

--- Elm 02 15.f01 (steady flow) ---

Flow Title=Multiple
Number of Profiles=7
Profile Names=10-year,25-year,50-year,1pct_min,100-year,1pct_plu,500-year
River Rch & RM= Elm 02 15,Reach-1,3524
      59      75      87      63     101     139     136
Boundary for River Rch & Prof#=Elm 02 15,Reach-1,1
Up Type=0
Dn Type=3
Dn Slope=0.001
Boundary for River Rch & Prof#=Elm 02 15,Reach-1,2
Up Type=0
Dn Type=3
Dn Slope=0.001
Boundary for River Rch & Prof#=Elm 02 15,Reach-1,3
Up Type=0
Dn Type=3
Dn Slope=0.001
Boundary for River Rch & Prof#=Elm 02 15,Reach-1,4
Up Type=0
Dn Type=3
Dn Slope=0.001
Boundary for River Rch & Prof#=Elm 02 15,Reach-1,5
Up Type=0
Dn Type=3
Dn Slope=0.001
Boundary for River Rch & Prof#=Elm 02 15,Reach-1,6
Up Type=0
Dn Type=3
Dn Slope=0.001
Boundary for River Rch & Prof#=Elm 02 15,Reach-1,7
Up Type=0
Dn Type=3
Dn Slope=0.001

--- Elm 02 15.g01 (geometry) ---

Geom Title=Existing Conditions

River Reach=Elm 02 15,Reach-1
Reach XY= 30
      1619005.00      6828388.00      1618889.81      6828338.45
      1618615.44      6828336.62      1618554.96      6828295.52
      1618460.59      6828343.55      1618399.17      6828490.85
      1618358.67      6828530.31      1618299.12      6828490.38
      1618220.28      6828488.39      1618144.50      6828536.78
      1617920.16      6828538.66      1617854.99      6828580.41
      1617770.42      6828538.15      1617694.50      6828586.76
      1617515.43      6828589.38      1617454.90      6828630.21
      1617405.08      6828595.83      1617315.63      6828637.36
      1617210.52      6828540.44      1617151.39      6828289.48
      1617057.44      6828193.52      1616956.59      6828184.17
      1616799.07      6828090.25      1616660.94      6828085.73
      1616444.45      6827989.10      1616360.97      6827990.17
      1616294.45      6828036.90      1616210.73      6828036.17
      1616160.13      6827990.95      1616155.00      6827938.00

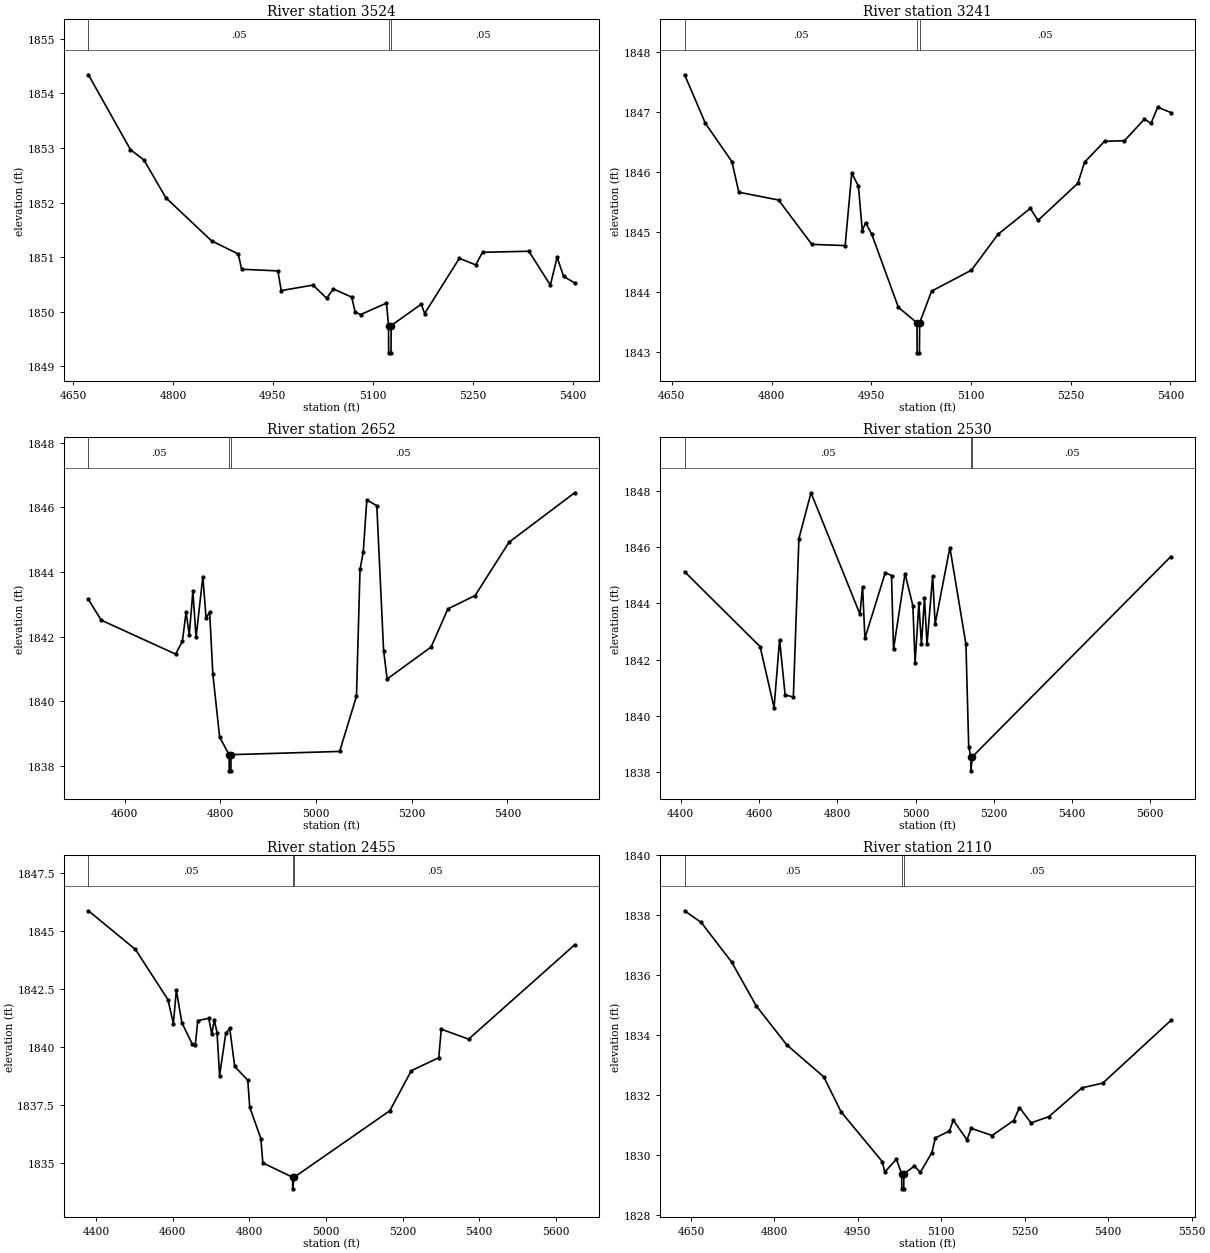
Type RM Length L Ch R = 1,3524,283,283,283
BEGIN DESCRIPTION:
Elm 02 15 3241.543
END DESCRIPTION:
XS GIS Cut Line= 3
      1619029.57      6828065.88      1618973.20      6828387.88
      1618897.78      6828783.86
#Sta/Elev= 30
  4673.1 1854.34  4736.2 1852.97  4756.5 1852.78  4789.3 1852.09  4858.0 1851.30
  4898.1 1851.06  4903.1 1850.78  4957.5 1850.75  4962.6 1850.39  5010.3 1850.49
  5030.7 1850.25  5040.8 1850.42  5068.4 1850.27  5073.5 1850.00  5081.6 1849.95
  5120.6 1850.16  5123.7 1849.75  5123.9 1849.25  5127.4 1849.25  5127.7 1849.75
  5172.8 1850.14  5177.9 1849.97  5230.0 1850.98  5254.6 1850.86  5264.8 1851.09
  5334.4 1851.11  5366.6 1850.49  5376.8 1851.00  5386.5 1850.65  5403.1 1850.53
#Mann=3,-1,0
  4673.1    0.05       0  5123.7    0.03       0  5127.7    0.05       0
Bank Sta=5123.7,5127.7
Exp/Cntr=0.3,0.1

Type RM Length L Ch R = 1,3241,589,589,589
BEGIN DESCRIPTION:
Elm 02 15 3241.36
END DESCRIPTION:
XS GIS Cut Line= 3
      1618724.01      6828006.88      1618706.65      6828338.46
      1618692.76      6828737.78
#Sta/Elev= 30
  4669.2 1847.62  4700.4 1846.81  4740.4 1846.17  4750.7 1845.66  4810.5 1845.53
  4860.6 1844.79  4910.7 1844.77  4920.7 1845.98  4930.7 1845.76  4936.5 1845.02
  4941.5 1845.15  4950.7 1844.96  4990.8 1843.74  5018.8 1843.48  5019.0 1842.98
  5022.5 1842.98  5022.8 1843.48  5040.8 1844.01  5100.8 1844.36  5140.9 1844.96
  5189.3 1845.39  5200.9 1845.19  5260.9 1845.81  5270.9 1846.16  5301.0 1846.51
  5331.0 1846.52  5361.0 1846.88  5371.0 1846.81  5381.0 1847.08  5400.8 1846.99
#Mann=3,-1,0
  4669.2    0.05       0  5018.8    0.03       0  5022.8    0.05       0
Bank Sta=5018.8,5022.8
Exp/Cntr=0.3,0.1

Type RM Length L Ch R = 1,2652,122,122,122
BEGIN DESCRIPTION:
Elm 02 15 2651.61
END DESCRIPTION:
XS GIS Cut Line= 4
      1618559.11      6828114.47      1618296.93      6828409.64
      1618276.10      6828489.50      1618640.37      6828886.73
#Sta/Elev= 30
  4524.2 1843.15  4551.0 1842.51  4706.5 1841.46  4720.7 1841.86  4728.3 1842.76
  4735.0 1842.06  4742.5 1843.40  4749.2 1841.98  4763.4 1843.86  4770.1 1842.58
  4777.6 1842.76  4784.3 1840.84  4798.5 1838.89  4818.3 1838.35  4818.5 1837.85
  4822.0 1837.85  4822.3 1838.35  5049.3 1838.45  5084.5 1840.16  5091.9 1844.08
  5098.7 1844.62  5106.1 1846.23  5127.0 1846.05  5141.2 1841.57  5148.6 1840.69
  5240.5 1841.68  5275.6 1842.86  5332.4 1843.27  5403.3 1844.92  5540.5 1846.45
#Mann=3,-1,0
  4524.2    0.05       0  4818.3    0.03       0  4822.3    0.05       0
Bank Sta=4818.3,4822.3
Exp/Cntr=0.3,0.1

Type RM Length L Ch R = 1,2530,75,75,75
BEGIN DESCRIPTION:
Elm 02 15 2529.9
END DESCRIPTION:
XS GIS Cut Line= 6
      1618480.99      6828071.07      1618258.74      6828305.47
      1618152.83      6828400.96      1618166.72      6828524.22
      1618232.70      6828578.04      1618588.58      6829020.73
#Sta/Elev= 30
  4409.8 1845.13  4602.8 1842.46  4638.4 1840.29  4652.5 1842.71  4666.7 1840.74
  4687.7 1840.67  4701.9 1846.31  4732.8 1847.94  4857.9 1843.62  4864.6 1844.60
  4870.6 1842.76  4922.8 1845.10  4938.6 1844.99  4943.7 1842.37  4973.1 1845.06
  4993.2 1843.92  4998.8 1841.88  5008.5 1844.00  5015.0 1842.55  5022.9 1844.18
  5029.3 1842.54  5043.7 1844.98  5050.1 1843.27  5087.8 1845.99  5128.8 1842.55
  5135.9 1838.90  5141.2 1838.54  5141.5 1838.04  5145.2 1838.54  5652.6 1845.67
#Mann=3,-1,0
  4409.8    0.05       0  5141.2    0.03       0  5145.2    0.05       0
Bank Sta=5141.2,5145.2
Exp/Cntr=0.3,0.1

Type RM Length L Ch R = 1,2455,345,345,345
BEGIN DESCRIPTION:
Elm 02 15 2454.87
END DESCRIPTION:
XS GIS Cut Line= 6
      1618383.71      6828053.76      1618119.85      6828272.49
      1618066.03      6828465.20      1618097.28      6828541.58
      1618204.92      6828699.57      1618496.59      6829046.80
#Sta/Elev= 30
  4379.4 1845.89  4502.3 1844.22  4587.0 1842.06  4601.3 1841.02  4609.1 1842.46
  4623.5 1841.06  4650.8 1840.13  4658.6 1840.10  4665.1 1841.15  4693.8 1841.25
  4701.6 1840.56  4708.1 1841.18  4715.4 1840.63  4722.0 1838.78  4738.2 1840.60
  4748.6 1840.81  4761.5 1839.17  4795.6 1838.58  4800.8 1837.41  4829.8 1836.06
  4835.0 1835.01  4912.7 1834.39  4913.0 1833.89  4916.7 1834.39  5166.6 1837.26
  5222.9 1838.99  5294.5 1839.55  5301.0 1840.78  5372.5 1840.35  5649.4 1844.42
#Mann=3,-1,0
  4379.4    0.05       0  4912.7    0.05       0  4916.7    0.05       0
Bank Sta=4912.7,4916.7
Exp/Cntr=0.3,0.1

Type RM Length L Ch R = 1,2110,666,666,666
BEGIN DESCRIPTION:
Elm 02 15 2109.85
END DESCRIPTION:
XS GIS Cut Line= 3
      1617930.49      6828211.46      1617776.42      6828541.30
      1617622.33      6829027.41
#Sta/Elev= 30
  4638.6 1838.15  4668.4 1837.76  4723.1 1836.44  4767.2 1834.98  4822.4 1833.67
  4888.6 1832.61  4919.8 1831.44  4993.8 1829.78  4998.4 1829.43  5019.4 1829.86
  5028.7 1829.37  5028.9 1828.87  5032.4 1828.87  5032.7 1829.37  5051.6 1829.63
  5062.2 1829.42  5083.1 1830.08  5089.2 1830.57  5114.6 1830.80  5121.5 1831.16
  5146.1 1830.51  5153.8 1830.89  5191.3 1830.65  5230.0 1831.15  5240.5 1831.58
  5261.4 1831.07  5293.4 1831.28  5352.7 1832.24  5390.3 1832.40  5512.6 1834.49
#Mann=3,-1,0
  4638.6    0.05       0  5028.7    0.03       0  5032.7    0.05       0
Bank Sta=5028.7,5032.7
Exp/Cntr=0.3,0.1

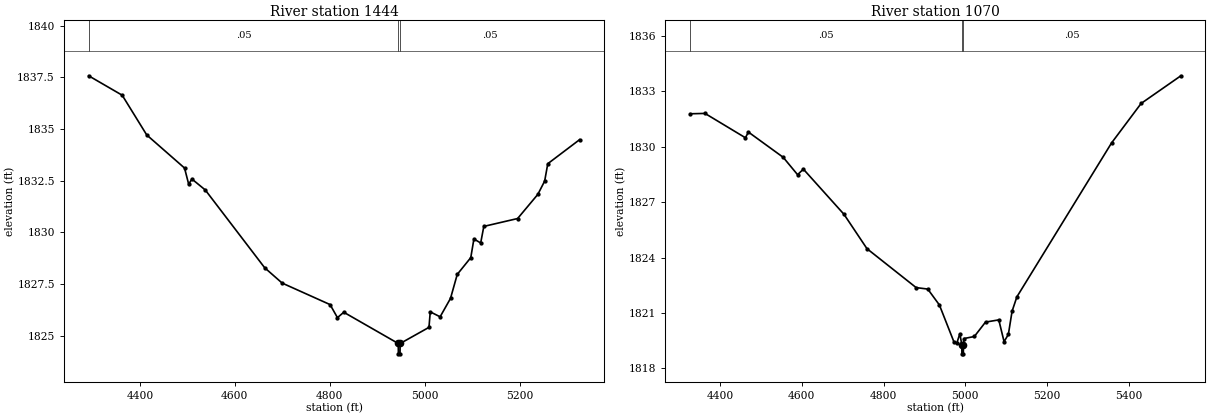
Type RM Length L Ch R = 1,1444,374,374,374
BEGIN DESCRIPTION:
Elm 02 15 1444.23
END DESCRIPTION:
XS GIS Cut Line= 3
      1617815.52      6828170.18      1617203.50      6828539.12
      1616993.02      6828779.99
#Sta/Elev= 30
  4292.0 1837.57  4362.7 1836.63  4414.4 1834.71  4494.1 1833.11  4502.8 1832.33
  4509.6 1832.58  4537.8 1832.05  4663.0 1828.29  4699.8 1827.55  4800.8 1826.51
  4816.3 1825.88  4829.7 1826.14  4944.5 1824.63  4944.7 1824.13  4948.2 1824.13
  4948.5 1824.63  5009.2 1825.41  5011.9 1826.16  5032.7 1825.92  5054.6 1826.81
  5068.8 1827.97  5097.3 1828.78  5103.9 1829.68  5118.2 1829.49  5124.8 1830.29
  5196.0 1830.67  5238.7 1831.84  5253.0 1832.48  5259.6 1833.32  5326.5 1834.48
#Mann=3,-1,0
  4292.0    0.05       0  4944.5    0.03       0  4948.5    0.05       0
Bank Sta=4944.5,4948.5
Exp/Cntr=0.3,0.1

Type RM Length L Ch R = 1,1070,0,0,0
BEGIN DESCRIPTION:
Elm 02 15 963.944
END DESCRIPTION:
XS GIS Cut Line= 3
      1617525.92      6827707.29      1617075.20      6828207.61
      1616918.26      6828710.80
#Sta/Elev= 30
  4326.6 1831.79  4363.3 1831.81  4462.2 1830.49  4469.4 1830.80  4554.6 1829.43
  4589.7 1828.49  4603.9 1828.79  4703.3 1826.34  4759.4 1824.48  4879.7 1822.37
  4908.1 1822.29  4936.5 1821.43  4972.4 1819.41  4979.1 1819.36  4986.6 1819.87
  4991.3 1819.28  4991.6 1818.78  4995.1 1818.78  4995.3 1819.28  4996.9 1819.61
  5022.0 1819.72  5049.3 1820.50  5081.8 1820.62  5094.7 1819.44  5105.2 1819.83
  5114.3 1821.09  5126.1 1821.87  5357.6 1830.21  5429.9 1832.35  5527.1 1833.85
#Mann=3,-1,0
  4326.6    0.05       0  4991.3    0.05       0  4995.3    0.05       0
Bank Sta=4991.3,4995.3
Exp/Cntr=0.3,0.1

Chan Stop Cuts=-1