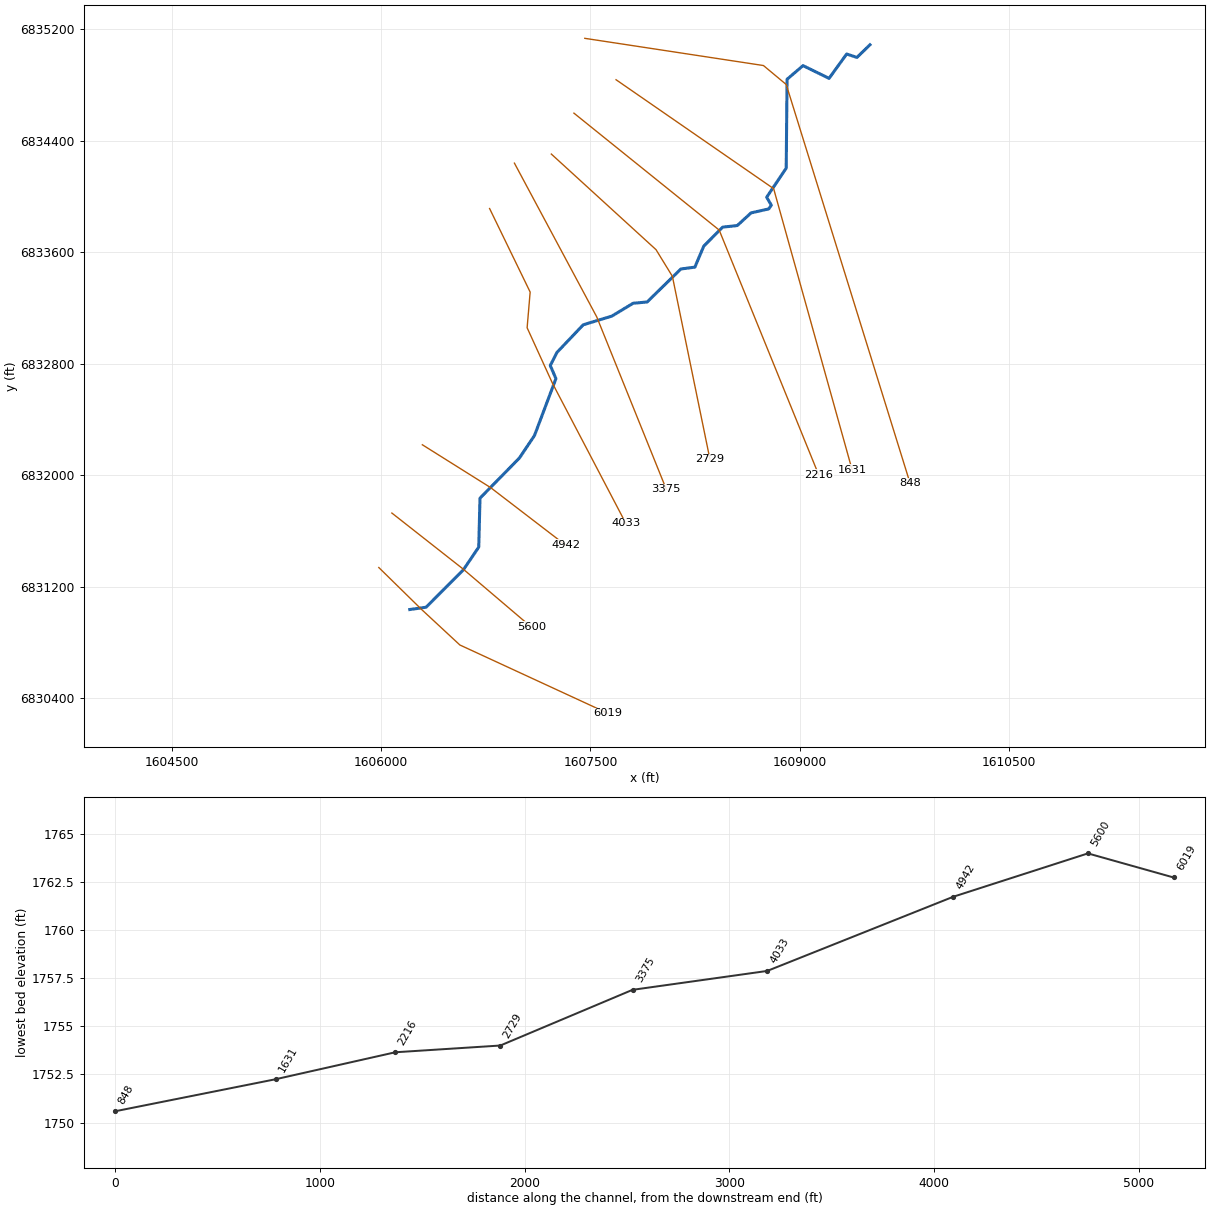
--- Elm 02 16.prj (project) ---

Proj Title=Elm 02 16 Base Level Engineering
Current Plan=p01
Default Exp/Contr=0.3,0.1
English Units
Geom File=g01
Flow File=f01
Plan File=p01
Y Axis Title=Elevation
X Axis Title(PF)=Main Channel Distance
X Axis Title(XS)=Station
BEGIN DESCRIPTION:
Elm 02 16
END DESCRIPTION:
DSS Export Rating Curves= 0
DSS Export Rating Curve Sorted= 0
DSS Export Volume Flow Curves= 0
DXF OffsetX= 0
DXF OffsetY= 0
DXF ScaleX= 1
DXF ScaleY= 10

--- Elm 02 16.p01 (plan) ---

Plan Title=Multiple Run
Short Identifier=Multiple
Geom File=g01
Flow File=f01
Subcritical Flow
K Sum by GR= 0
Std Step Tol= 0.01
Critical Tol= 0.01
Num of Std Step Trials= 20
Max Error Tol= 0.3
Flow Tol Ratio= 0.001
Split Flow NTrial= 30
Split Flow Tol= 0.02
Split Flow Ratio= 0.02
Log Output Level= 0
Friction Slope Method= 1
Unsteady Friction Slope Method= 2
Unsteady Bridges Friction Slope Method= 1
Parabolic Critical Depth
Global Vel Dist=  1 , 1 , 1
Global Log Level= 0
CheckData=True
Encroach Param= -1, 0, 0, 0
BEGIN DESCRIPTION:
Multiple Run
END DESCRIPTION:

--- Elm 02 16.f01 (steady flow) ---

Flow Title=Multiple
Program Version=4.10
Number of Profiles= 7
Profile Names=10-year,25-year,50-year,1pct_min,100-year,1pct_plu,500-year
River Rch & RM=Elm 02 16,Reach-1         ,6019
     192     260     315     237     380     523     560
River Rch & RM=Elm 02 16,Reach-1         ,4033
     280     388     477     363     581     800     876
Boundary for River Rch & Prof#=Elm 02 16,Reach-1         , 1
Up Type= 0
Dn Type= 3
Dn Slope=0.002
Boundary for River Rch & Prof#=Elm 02 16,Reach-1         , 2
Up Type= 0
Dn Type= 3
Dn Slope=0.002
Boundary for River Rch & Prof#=Elm 02 16,Reach-1         , 3
Up Type= 0
Dn Type= 3
Dn Slope=0.002
Boundary for River Rch & Prof#=Elm 02 16,Reach-1         , 4
Up Type= 0
Dn Type= 3
Dn Slope=0.002
Boundary for River Rch & Prof#=Elm 02 16,Reach-1         , 5
Up Type= 0
Dn Type= 3
Dn Slope=0.002
Boundary for River Rch & Prof#=Elm 02 16,Reach-1         , 6
Up Type= 0
Dn Type= 3
Dn Slope=0.002
Boundary for River Rch & Prof#=Elm 02 16,Reach-1         , 7
Up Type= 0
Dn Type= 3
Dn Slope=0.002
DSS Import GetInterval= 0
DSS Import GetPeak= 0
DSS Import FillOption= 0

--- Elm 02 16.g01 (geometry) ---

Geom Title=Existing Conditions

River Reach=Elm 02 16,Reach-1
Reach XY= 30
      1606205.00      6831038.00      1606321.76      6831054.43
      1606588.35      6831321.33      1606699.53      6831485.55
      1606708.54      6831836.54      1606991.37      6832124.79
      1607099.16      6832285.71      1607253.02      6832693.73
      1607212.55      6832788.03      1607260.92      6832882.23
      1607448.94      6833079.86      1607653.42      6833141.83
      1607806.59      6833234.17      1607907.43      6833243.52
      1608148.88      6833480.12      1608249.56      6833493.25
      1608313.14      6833644.05      1608448.83      6833780.14
      1608553.50      6833791.63      1608652.59      6833882.46
      1608779.41      6833910.88      1608797.54      6833937.76
      1608764.32      6833994.65      1608904.49      6834203.21
      1608910.45      6834840.47      1609025.13      6834938.41
      1609211.75      6834847.10      1609337.96      6835021.77
      1609411.66      6834997.18      1609505.00      6835088.00

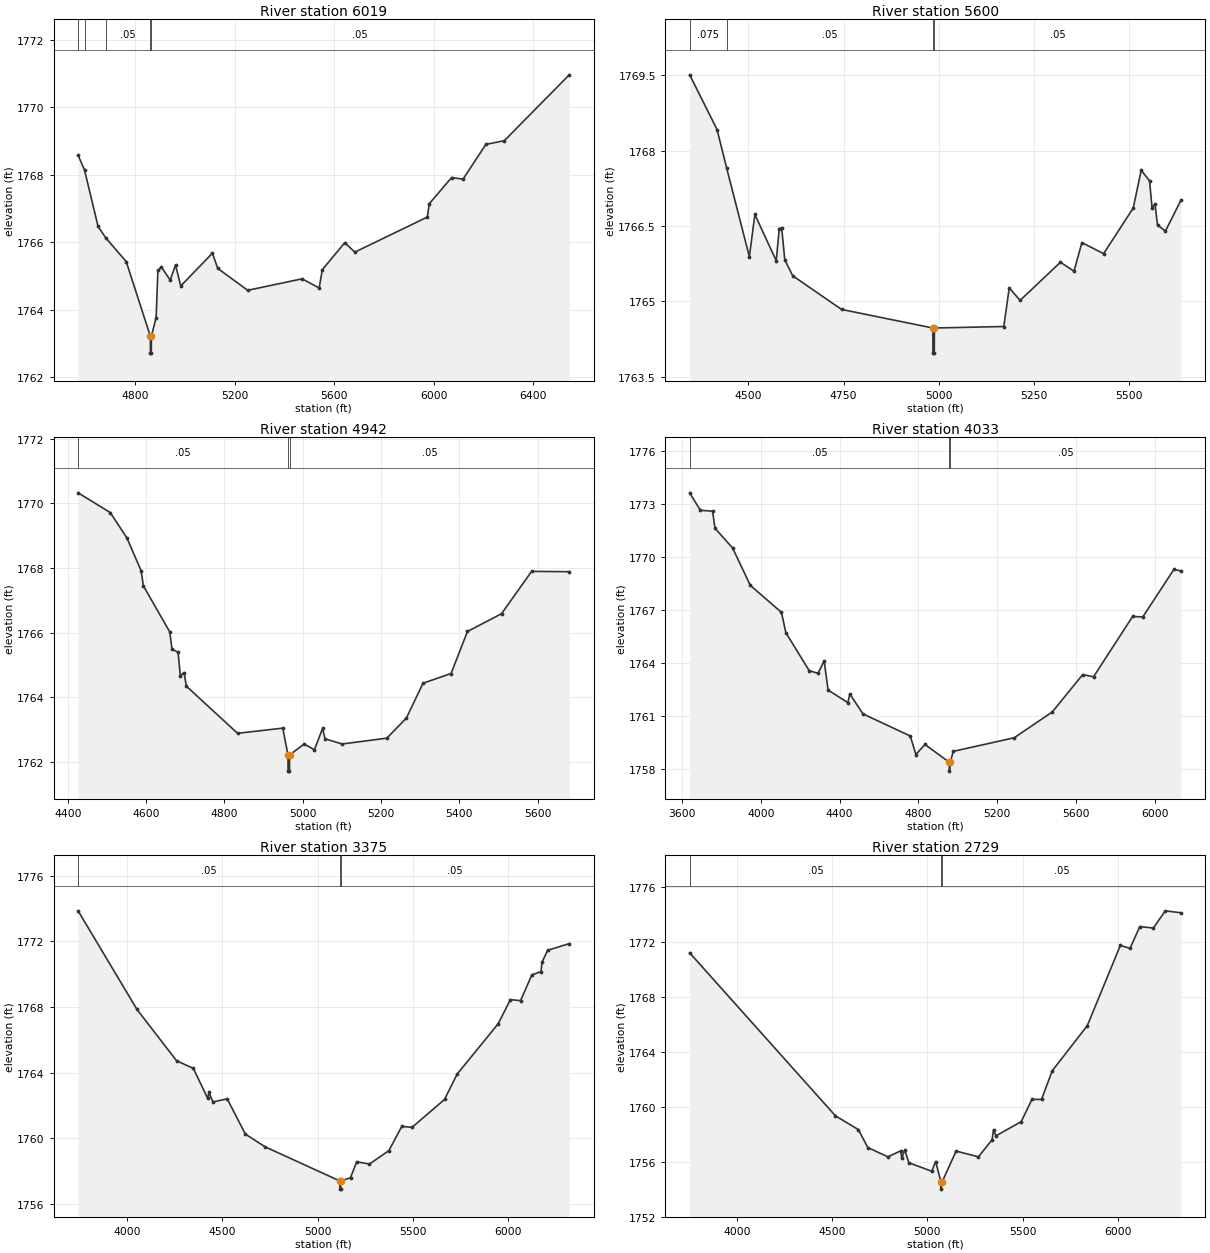
Type RM Length L Ch R = 1,6019,419,419,419
BEGIN DESCRIPTION:
Elm 02 16 5605.245
END DESCRIPTION:
XS GIS Cut Line= 4
      1605982.76      6831339.29      1606289.95      6831038.12
      1606564.17      6830783.72      1607626.14      6830293.27
#Sta/Elev= 30
  4569.8 1768.58  4595.7 1768.14  4650.1 1766.47  4681.3 1766.13  4763.2 1765.43
  4860.2 1763.22  4860.5 1762.72  4864.0 1762.72  4864.2 1763.22  4883.4 1763.77
  4890.5 1765.17  4904.7 1765.27  4940.0 1764.88  4961.3 1765.33  4982.4 1764.71
  5109.8 1765.68  5130.8 1765.23  5251.5 1764.58  5469.9 1764.92  5538.7 1764.65
  5551.2 1765.19  5641.5 1765.99  5681.9 1765.71  5973.7 1766.75  5980.8 1767.14
  6070.9 1767.92  6116.8 1767.87  6208.6 1768.90  6282.9 1769.01  6543.8 1770.96
#Mann=5,-1,0
  4569.8   0.075       0  4595.7     0.1       0  4681.3    0.05       0
  4860.2    0.05       0  4864.2    0.05       0
Bank Sta=4860.2,4864.2
Exp/Cntr=0.3,0.1

Type RM Length L Ch R = 1,5600,658,658,658
BEGIN DESCRIPTION:
Elm 02 16 5600.39
END DESCRIPTION:
XS GIS Cut Line= 3
      1606076.52      6831729.91      1606586.93      6831328.87
      1607076.06      6830912.59
#Sta/Elev= 30
  4345.4 1769.51  4417.4 1768.42  4442.7 1767.65  4502.3 1765.89  4516.8 1766.73
  4572.9 1765.81  4581.0 1766.45  4587.3 1766.46  4595.4 1765.83  4616.2 1765.51
  4744.6 1764.84  4984.8 1764.47  4985.0 1763.97  4988.5 1763.97  4988.8 1764.47
  5171.3 1764.50  5185.6 1765.27  5214.1 1765.02  5320.3 1765.78  5355.8 1765.60
  5376.6 1766.17  5433.7 1765.95  5511.7 1766.86  5532.5 1767.61  5554.5 1767.40
  5561.1 1766.86  5568.8 1766.94  5575.4 1766.52  5596.2 1766.40  5636.8 1767.01
#Mann=4,-1,0
  4345.4   0.075       0  4442.7    0.05       0  4984.8    0.05       0
  4988.8    0.05       0
Bank Sta=4984.8,4988.8
Exp/Cntr=0.3,0.1

Type RM Length L Ch R = 1,4942,909,909,909
BEGIN DESCRIPTION:
Elm 02 16 4942.34
END DESCRIPTION:
XS GIS Cut Line= 3
      1606295.25      6832219.50      1606784.85      6831912.20
      1607321.29      6831500.76
#Sta/Elev= 30
  4426.5 1770.33  4508.5 1769.72  4550.9 1768.94  4587.4 1767.92  4593.3 1767.45
  4660.4 1766.03  4666.3 1765.49  4681.7 1765.40  4687.6 1764.67  4697.0 1764.77
  4702.9 1764.35  4833.6 1762.89  4949.1 1763.05  4962.4 1762.22  4962.7 1761.72
  4966.2 1761.72  4966.4 1762.22  5003.8 1762.56  5029.9 1762.38  5050.7 1763.04
  5057.0 1762.72  5100.5 1762.56  5214.8 1762.74  5264.6 1763.36  5307.2 1764.44
  5378.8 1764.74  5420.6 1766.04  5507.6 1766.59  5584.5 1767.90  5680.6 1767.89
#Mann=3,-1,0
  4426.5    0.05       0  4962.4    0.05       0  4966.4    0.05       0
Bank Sta=4962.4,4966.4
Exp/Cntr=0.3,0.1

Type RM Length L Ch R = 1,4033,658,658,658
BEGIN DESCRIPTION:
Elm 02 16 4032.73
END DESCRIPTION:
XS GIS Cut Line= 5
      1606777.38      6833913.64      1607068.18      6833314.68
      1607046.48      6833058.60      1607228.77      6832659.30
      1607753.95      6831656.68
#Sta/Elev= 30
  3638.7 1773.63  3692.7 1772.64  3754.9 1772.59  3767.3 1771.62  3856.3 1770.51
  3946.5 1768.39  4104.5 1766.86  4127.0 1765.71  4245.4 1763.56  4290.5 1763.41
  4321.3 1764.12  4341.3 1762.46  4441.7 1761.75  4451.7 1762.24  4518.4 1761.11
  4758.6 1759.86  4787.1 1758.81  4833.2 1759.38  4957.0 1758.37  4957.3 1757.87
  4961.6 1758.37  4976.9 1758.99  5286.5 1759.76  5479.5 1761.22  5634.1 1763.34
  5688.8 1763.21  5887.4 1766.63  5938.9 1766.60  6096.8 1769.29  6132.3 1769.21
#Mann=3,-1,0
  3638.7    0.05       0  4957.0    0.05       0  4961.6    0.05       0
Bank Sta=4957,4961.6
Exp/Cntr=0.3,0.1

Type RM Length L Ch R = 1,3375,646,646,646
BEGIN DESCRIPTION:
Elm 02 16 3375.13
END DESCRIPTION:
XS GIS Cut Line= 3
      1606955.34      6834239.14      1607545.61      6833136.73
      1608044.08      6831901.40
#Sta/Elev= 30
  3741.2 1773.87  4051.0 1767.85  4259.1 1764.72  4346.8 1764.26  4423.1 1762.42
  4428.9 1762.79  4450.8 1762.21  4525.2 1762.40  4620.6 1760.25  4724.6 1759.47
  5117.3 1757.39  5117.7 1756.89  5121.8 1756.89  5122.1 1757.39  5173.6 1757.59
  5206.0 1758.56  5273.4 1758.42  5375.3 1759.24  5443.2 1760.72  5497.1 1760.66
  5667.9 1762.36  5734.4 1763.91  5950.0 1766.98  6014.1 1768.45  6067.8 1768.39
  6126.9 1769.96  6175.2 1770.16  6180.6 1770.74  6210.1 1771.46  6323.8 1771.87
#Mann=3,-1,0
  3741.2    0.05       0  5117.3    0.05       0  5122.1    0.05       0
Bank Sta=5117.3,5122.1
Exp/Cntr=0.3,0.1

Type RM Length L Ch R = 1,2729,513,513,513
BEGIN DESCRIPTION:
Elm 02 16 2729.19
END DESCRIPTION:
XS GIS Cut Line= 4
      1607220.09      6834304.27      1607970.96      6833618.50
      1608088.15      6833427.52      1608357.25      6832116.73
#Sta/Elev= 30
  3752.4 1771.20  4517.5 1759.34  4638.3 1758.33  4687.6 1757.03  4793.3 1756.35
  4860.5 1756.79  4866.3 1756.25  4881.8 1756.86  4903.1 1755.92  5023.5 1755.30
  5043.9 1756.01  5072.1 1754.50  5072.4 1754.00  5077.0 1754.50  5151.4 1756.77
  5268.5 1756.35  5340.0 1757.59  5347.9 1758.33  5360.4 1757.88  5493.1 1758.91
  5549.4 1760.53  5599.8 1760.53  5656.4 1762.62  5840.2 1765.90  6013.7 1771.74
  6064.8 1771.53  6115.8 1773.11  6187.3 1773.01  6249.7 1774.26  6331.5 1774.12
#Mann=3,-1,0
  3752.4    0.05       0  5072.1    0.05       0  5077.0    0.05       0
Bank Sta=5072.1,5077
Exp/Cntr=0.3,0.1

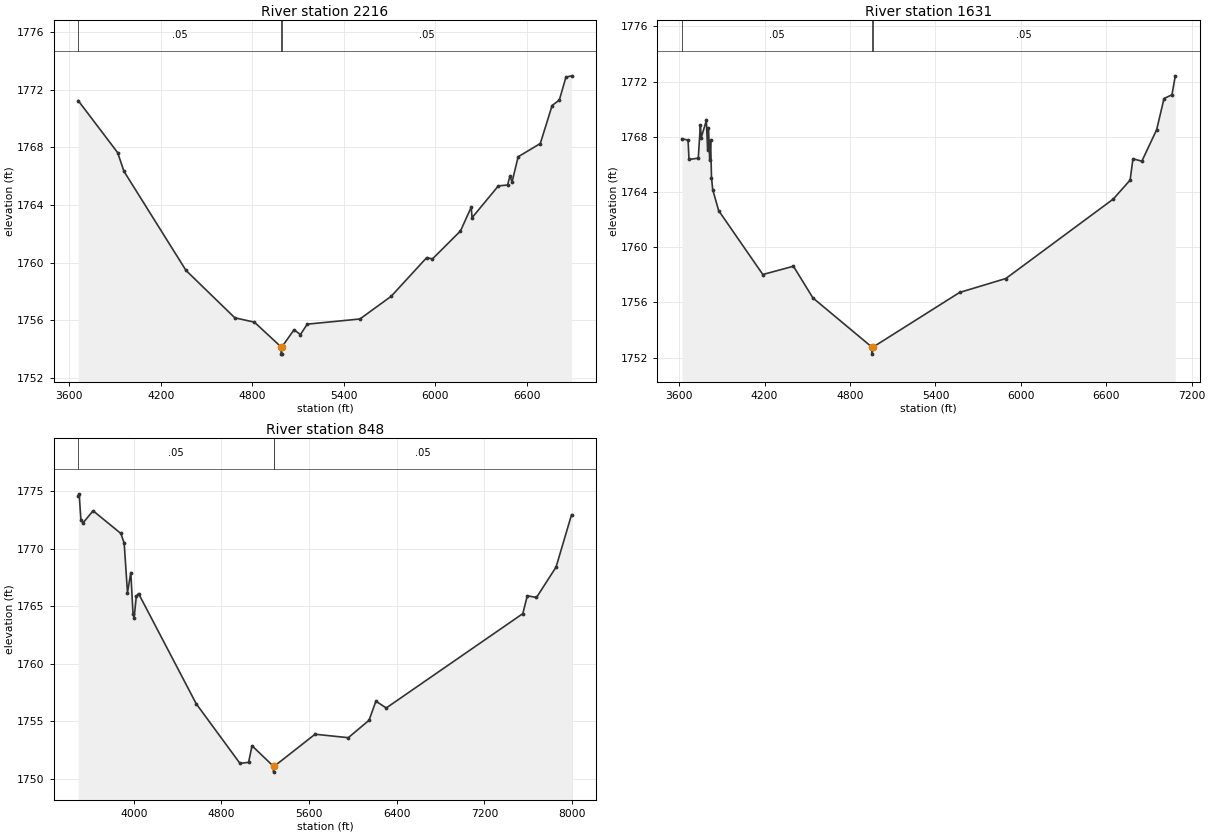
Type RM Length L Ch R = 1,2216,585,585,585
BEGIN DESCRIPTION:
Elm 02 16 2216.46
END DESCRIPTION:
XS GIS Cut Line= 3
      1607382.11      6834597.68      1608423.80      6833759.12
      1609137.35      6832003.88
#Sta/Elev= 30
  3659.6 1771.25  3917.9 1767.64  3959.5 1766.34  4365.8 1759.46  4685.8 1756.17
  4813.8 1755.87  4988.8 1754.15  4989.2 1753.65  4993.4 1753.65  4993.8 1754.15
  5073.6 1755.34  5115.5 1755.01  5160.0 1755.73  5505.4 1756.09  5710.5 1757.67
  5942.7 1760.35  5980.4 1760.26  6163.9 1762.20  6234.4 1763.85  6239.8 1763.12
  6412.2 1765.33  6472.7 1765.39  6487.7 1766.01  6502.1 1765.61  6541.7 1767.35
  6686.8 1768.27  6764.4 1770.91  6811.6 1771.29  6854.8 1772.88  6891.6 1772.97
#Mann=3,-1,0
  3659.6    0.05       0  4988.8    0.05       0  4993.8    0.05       0
Bank Sta=4988.8,4993.8
Exp/Cntr=0.3,0.1

Type RM Length L Ch R = 1,1631,783,783,783
BEGIN DESCRIPTION:
Elm 02 16 1630.54
END DESCRIPTION:
XS GIS Cut Line= 3
      1607684.24      6834837.23      1608814.42      6834056.00
      1609376.56      6832041.68
#Sta/Elev= 30
  3619.4 1767.86  3662.4 1767.76  3669.0 1766.36  3734.1 1766.45  3749.0 1768.87
  3755.0 1767.94  3790.9 1769.19  3799.7 1767.05  3805.7 1768.67  3814.5 1766.29
  3820.6 1767.77  3827.0 1765.05  3835.5 1764.17  3877.4 1762.65  4187.6 1758.02
  4402.5 1758.62  4539.7 1756.32  4954.8 1752.75  4955.2 1752.25  4960.0 1752.75
  5569.8 1756.72  5894.5 1757.73  6649.1 1763.49  6767.2 1764.86  6787.3 1766.41
  6849.6 1766.23  6953.6 1768.51  7005.4 1770.77  7061.3 1771.05  7084.6 1772.42
#Mann=3,-1,0
  3619.4    0.05       0  4954.8    0.05       0  4960.0    0.05       0
Bank Sta=4954.8,4960
Exp/Cntr=0.3,0.1

Type RM Length L Ch R = 1,848,0,0,0
BEGIN DESCRIPTION:
Elm 02 16 1448.13
END DESCRIPTION:
XS GIS Cut Line= 4
      1607460.21      6835134.13      1608741.14      6834939.11
      1608904.51      6834803.21      1609793.34      6831942.19
#Sta/Elev= 30
  3491.8 1774.56  3500.5 1774.75  3516.9 1772.44  3537.1 1772.24  3627.6 1773.28
  3881.0 1771.31  3911.4 1770.48  3941.7 1766.17  3972.1 1767.92  3992.3 1764.30
  4002.4 1764.00  4022.6 1765.88  4042.9 1766.09  4568.9 1756.53  4968.6 1751.35
  5047.2 1751.44  5078.8 1752.88  5275.0 1751.09  5275.5 1750.59  5280.4 1751.09
  5654.2 1753.88  5957.7 1753.58  6146.8 1755.09  6209.7 1756.75  6304.2 1756.16
  7550.9 1764.35  7591.9 1765.90  7675.7 1765.75  7854.4 1768.39  7995.9 1772.94
#Mann=3,-1,0
  3491.8    0.05       0  5275.0    0.05       0  5280.4    0.05       0
Bank Sta=5275,5280.4
Exp/Cntr=0.3,0.1

Chan Stop Cuts=-1