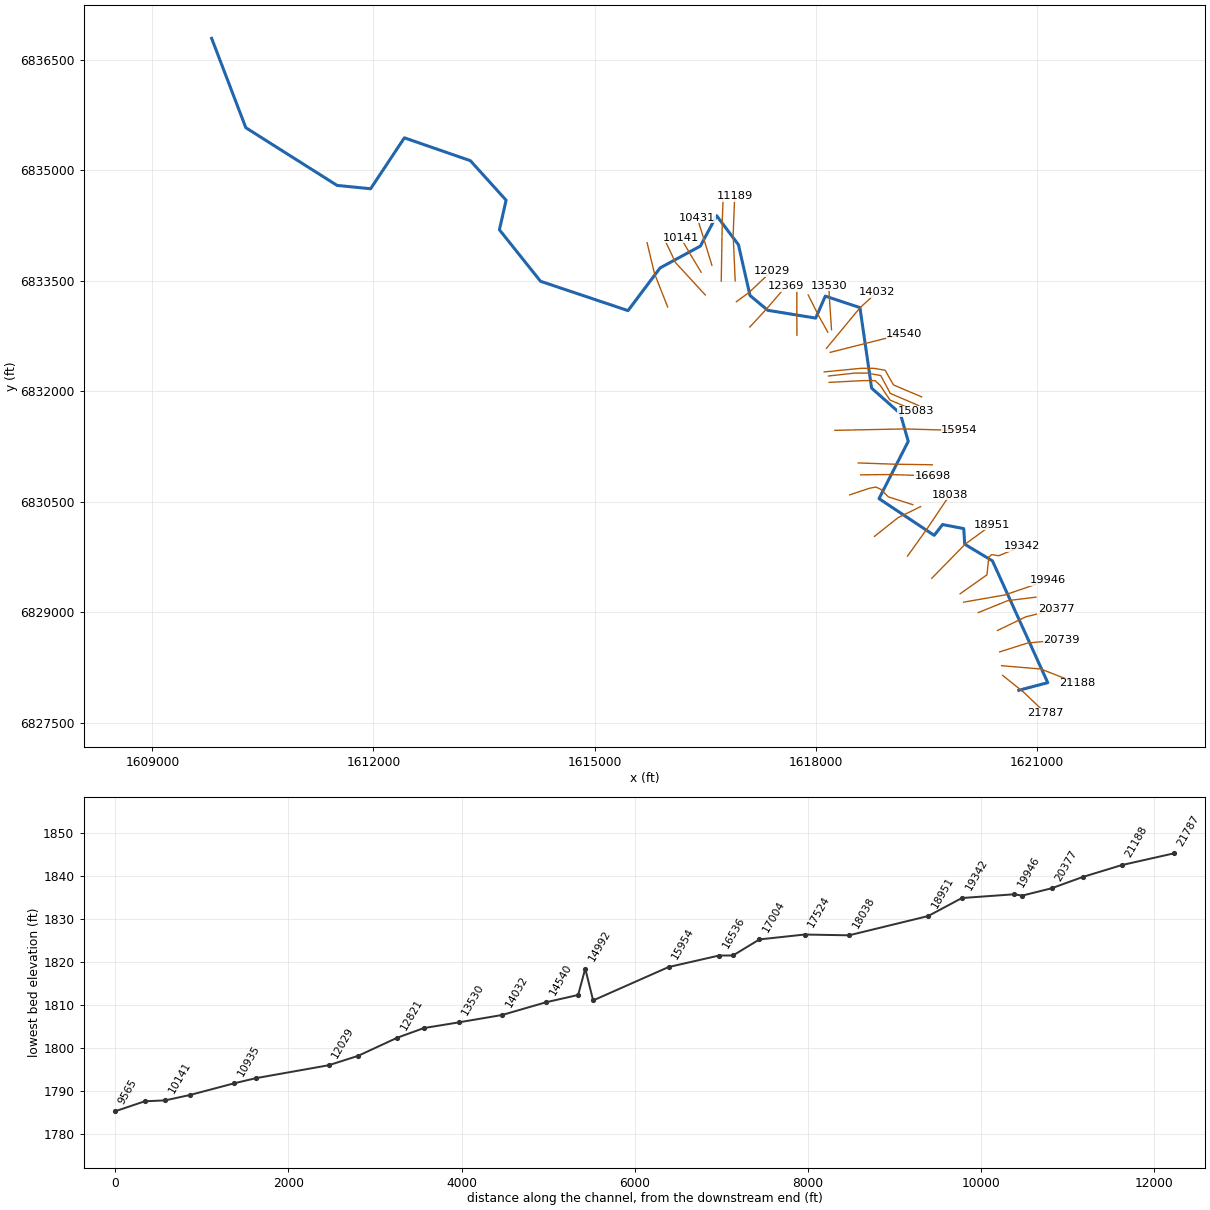
--- Elm 02 17.prj (project) ---

Proj Title=Elm 02 17 Base Level Engineering
Current Plan=p01
Default Exp/Contr=0.3,0.1
English Units
Geom File=g01
Flow File=f01
Plan File=p01
BEGIN DESCRIPTION:
Elm 02 17
END DESCRIPTION:

--- Elm 02 17.p01 (plan) ---

Plan Title=Multiple Run
Short Identifier=Multiple
Geom File=g01
Flow File=f01
Subcritical Flow
K Sum by GR= 0
Std Step Tol= 0.01
Critical Tol= 0.01
Num of Std Step Trials= 20
Max Error Tol= 0.3
Flow Tol Ratio= 0.001
Split Flow NTrial= 30
Split Flow Tol= 0.02
Split Flow Ratio= 0.02
Log Output Level= 0
Friction Slope Method= 1
Unsteady Friction Slope Method= 2
Unsteady Bridges Friction Slope Method= 1
Parabolic Critical Depth
Global Vel Dist=  1 , 1 , 1
Global Log Level= 0
CheckData=True
Encroach Param= -1, 0, 0, 0
BEGIN DESCRIPTION:
Multiple Run
END DESCRIPTION:

--- Elm 02 17.f01 (steady flow) ---

Flow Title=Multiple
Number of Profiles=7
Profile Names=10-year,25-year,50-year,1pct_min,100-year,1pct_plu,500-year
River Rch & RM= Elm 02 17,Reach-1,21787
     167     225     272     204     327     450     478
River Rch & RM= Elm 02 17,Reach-1,20739
     305     425     525     401     643     885     979
River Rch & RM= Elm 02 17,Reach-1,12029
     422     598     746     576     922    1270    1430
Boundary for River Rch & Prof#=Elm 02 17,Reach-1,1
Up Type=0
Dn Type=3
Dn Slope=0.001
Boundary for River Rch & Prof#=Elm 02 17,Reach-1,2
Up Type=0
Dn Type=3
Dn Slope=0.001
Boundary for River Rch & Prof#=Elm 02 17,Reach-1,3
Up Type=0
Dn Type=3
Dn Slope=0.001
Boundary for River Rch & Prof#=Elm 02 17,Reach-1,4
Up Type=0
Dn Type=3
Dn Slope=0.001
Boundary for River Rch & Prof#=Elm 02 17,Reach-1,5
Up Type=0
Dn Type=3
Dn Slope=0.001
Boundary for River Rch & Prof#=Elm 02 17,Reach-1,6
Up Type=0
Dn Type=3
Dn Slope=0.001
Boundary for River Rch & Prof#=Elm 02 17,Reach-1,7
Up Type=0
Dn Type=3
Dn Slope=0.001

--- Elm 02 17.g01 (geometry) ---

Geom Title=Existing Conditions

River Reach=Elm 02 17,Reach-1
Reach XY= 30
      1620755.00      6827938.00      1621147.48      6828041.12
      1620397.12      6829694.13      1620021.03      6829920.86
      1620007.77      6830132.64      1619720.64      6830187.58
      1619606.67      6830041.08      1618858.37      6830539.28
      1619255.17      6831317.74      1619146.86      6831694.06
      1618758.04      6832039.42      1618599.59      6833132.83
      1618129.79      6833288.36      1617999.57      6832990.17
      1617348.94      6833096.14      1617108.51      6833296.48
      1616951.18      6833986.42      1616655.07      6834380.73
      1616435.22      6833967.91      1615888.32      6833671.36
      1615453.42      6833091.67      1614266.31      6833490.26
      1613708.67      6834189.59      1613799.54      6834590.45
      1613314.68      6835127.24      1612419.76      6835437.25
      1611961.17      6834745.86      1611506.50      6834791.62
      1610268.61      6835574.76      1609805.00      6836788.00

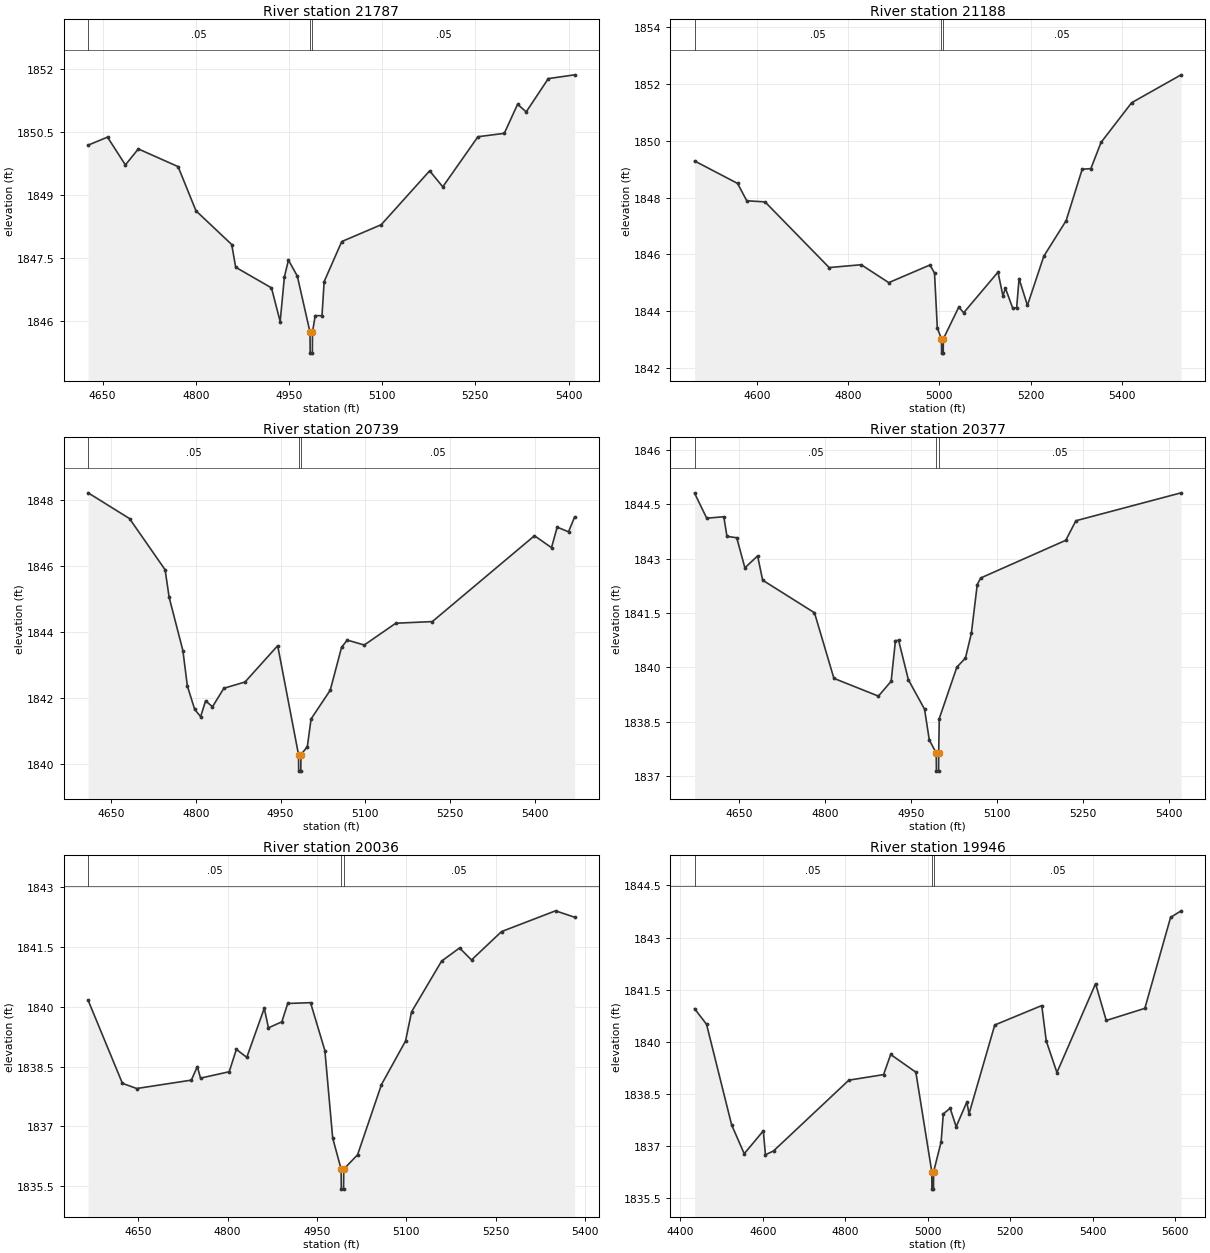
Type RM Length L Ch R = 1,21787,599,599,599
BEGIN DESCRIPTION:
Elm 02 17 21387.972
END DESCRIPTION:
XS GIS Cut Line= 3
      1620534.16      6828141.28      1620824.98      6827907.40
      1621121.33      6827624.36
#Sta/Elev= 30
  4626.8 1850.18  4658.0 1850.37  4686.8 1849.71  4707.6 1850.09  4771.6 1849.67
  4800.4 1848.62  4857.9 1847.82  4864.3 1847.28  4921.9 1846.79  4935.9 1845.99
  4942.7 1847.05  4949.2 1847.45  4963.5 1847.07  4983.9 1845.74  4984.2 1845.24
  4987.7 1845.24  4987.9 1845.74  4992.3 1846.13  5003.2 1846.13  5006.7 1846.94
  5035.0 1847.89  5098.5 1848.29  5176.5 1849.57  5197.6 1849.19  5254.2 1850.38
  5296.6 1850.46  5318.0 1851.15  5331.9 1850.97  5367.4 1851.76  5409.8 1851.85
#Mann=3,-1,0
  4626.8    0.05       0  4983.9    0.05       0  4987.9    0.05       0
Bank Sta=4983.9,4987.9
Exp/Cntr=0.3,0.1

Type RM Length L Ch R = 1,21188,449,449,449
BEGIN DESCRIPTION:
Elm 02 17 21188.43
END DESCRIPTION:
XS GIS Cut Line= 3
      1620521.12      6828271.52      1621052.35      6828227.25
      1621548.40      6828032.47
#Sta/Elev= 30
  4463.9 1849.29  4558.1 1848.50  4578.2 1847.89  4618.3 1847.85  4758.8 1845.54
  4829.0 1845.64  4889.3 1845.01  4979.6 1845.63  4989.6 1845.35  4995.8 1843.41
  5004.9 1843.03  5005.2 1842.53  5008.7 1842.53  5008.9 1843.03  5042.8 1844.15
  5053.5 1843.95  5128.7 1845.38  5139.5 1844.55  5145.1 1844.81  5161.0 1844.11
  5169.6 1844.13  5174.9 1845.15  5193.2 1844.21  5229.1 1845.94  5278.0 1847.19
  5313.2 1849.00  5332.2 1849.02  5354.4 1849.94  5421.6 1851.34  5529.9 1852.32
#Mann=3,-1,0
  4463.9    0.05       0  5004.9    0.05       0  5008.9    0.05       0
Bank Sta=5004.9,5008.9
Exp/Cntr=0.3,0.1

Type RM Length L Ch R = 1,20739,362,362,362
BEGIN DESCRIPTION:
Elm 02 17 20739.47
END DESCRIPTION:
XS GIS Cut Line= 3
      1620495.09      6828459.03      1620872.66      6828578.81
      1621335.74      6828623.04
#Sta/Elev= 30
  4609.2 1848.21  4682.5 1847.43  4745.5 1845.88  4752.7 1845.04  4777.0 1843.43
  4784.9 1842.36  4797.9 1841.65  4808.4 1841.43  4817.2 1841.91  4829.4 1841.73
  4849.5 1842.29  4887.0 1842.48  4944.8 1843.58  4981.7 1840.28  4982.0 1839.78
  4985.7 1839.78  4986.0 1840.28  4997.3 1840.52  5003.9 1841.36  5037.8 1842.23
  5057.9 1843.53  5067.9 1843.75  5098.1 1843.60  5153.9 1844.26  5218.6 1844.31
  5399.4 1846.91  5429.6 1846.55  5439.6 1847.17  5459.7 1847.03  5470.5 1847.48
#Mann=3,-1,0
  4609.2    0.05       0  4981.7    0.05       0  4986.0    0.05       0
Bank Sta=4981.7,4986
Exp/Cntr=0.3,0.1

Type RM Length L Ch R = 1,20377,341,341,341
BEGIN DESCRIPTION:
Elm 02 17 20377.45
END DESCRIPTION:
XS GIS Cut Line= 3
      1620465.91      6828749.97      1620851.32      6828935.73
      1621260.50      6829036.29
#Sta/Elev= 30
  4571.9 1844.81  4593.1 1844.12  4622.9 1844.16  4628.4 1843.62  4645.5 1843.58
  4659.7 1842.75  4681.9 1843.08  4690.7 1842.41  4781.2 1841.51  4815.1 1839.70
  4892.8 1839.21  4915.0 1839.62  4922.5 1840.74  4928.0 1840.75  4945.1 1839.66
  4973.3 1838.85  4981.6 1838.00  4993.7 1837.64  4994.0 1837.14  4997.8 1837.14
  4998.0 1837.64  4999.0 1838.59  5029.7 1840.01  5044.7 1840.26  5055.0 1840.94
  5065.3 1842.29  5071.3 1842.47  5219.8 1843.51  5237.5 1844.05  5421.1 1844.82
#Mann=3,-1,0
  4571.9    0.05       0  4993.7    0.05       0  4998.0    0.05       0
Bank Sta=4993.7,4998
Exp/Cntr=0.3,0.1

Type RM Length L Ch R = 1,20036,90,90,90
BEGIN DESCRIPTION:
Elm 02 17 20035.92
END DESCRIPTION:
XS GIS Cut Line= 3
      1620204.32      6828992.31      1620605.40      6829155.09
      1620986.88      6829201.96
#Sta/Elev= 30
  4565.6 1840.16  4623.2 1838.08  4647.2 1837.95  4739.0 1838.16  4749.0 1838.50
  4754.4 1838.21  4802.6 1838.37  4814.6 1838.93  4832.1 1838.73  4861.5 1839.96
  4868.5 1839.47  4891.0 1839.62  4900.9 1840.08  4939.2 1840.10  4963.3 1838.90
  4976.4 1836.71  4990.6 1835.93  4990.9 1835.43  4994.7 1835.43  4995.0 1835.93
  5018.2 1836.29  5058.4 1838.05  5098.8 1839.14  5108.9 1839.87  5159.3 1841.14
  5189.5 1841.47  5209.6 1841.17  5260.0 1841.88  5350.7 1842.40  5382.8 1842.24
#Mann=3,-1,0
  4565.6    0.05       0  4990.6    0.05       0  4995.0    0.05       0
Bank Sta=4990.6,4995
Exp/Cntr=0.3,0.1

Type RM Length L Ch R = 1,19946,604,604,604
BEGIN DESCRIPTION:
Elm 02 17 19945.79
END DESCRIPTION:
XS GIS Cut Line= 3
      1620006.43      6829134.25      1620566.34      6829231.91
      1621144.51      6829431.14
#Sta/Elev= 30
  4434.5 1840.95  4463.5 1840.50  4524.4 1837.60  4554.9 1836.77  4601.2 1837.43
  4606.3 1836.74  4625.9 1836.85  4808.6 1838.89  4892.8 1839.05  4910.1 1839.63
  4971.1 1839.12  5009.8 1836.25  5010.1 1835.75  5013.9 1835.75  5014.2 1836.25
  5032.4 1837.11  5037.7 1837.92  5054.3 1838.08  5068.9 1837.55  5094.8 1838.26
  5100.1 1837.92  5162.5 1840.48  5276.5 1841.04  5287.4 1840.02  5313.3 1839.11
  5407.0 1841.67  5432.9 1840.61  5526.5 1840.96  5588.9 1843.58  5614.4 1843.77
#Mann=3,-1,0
  4434.5    0.05       0  5009.8    0.05       0  5014.2    0.05       0
Bank Sta=5009.8,5014.2
Exp/Cntr=0.3,0.1

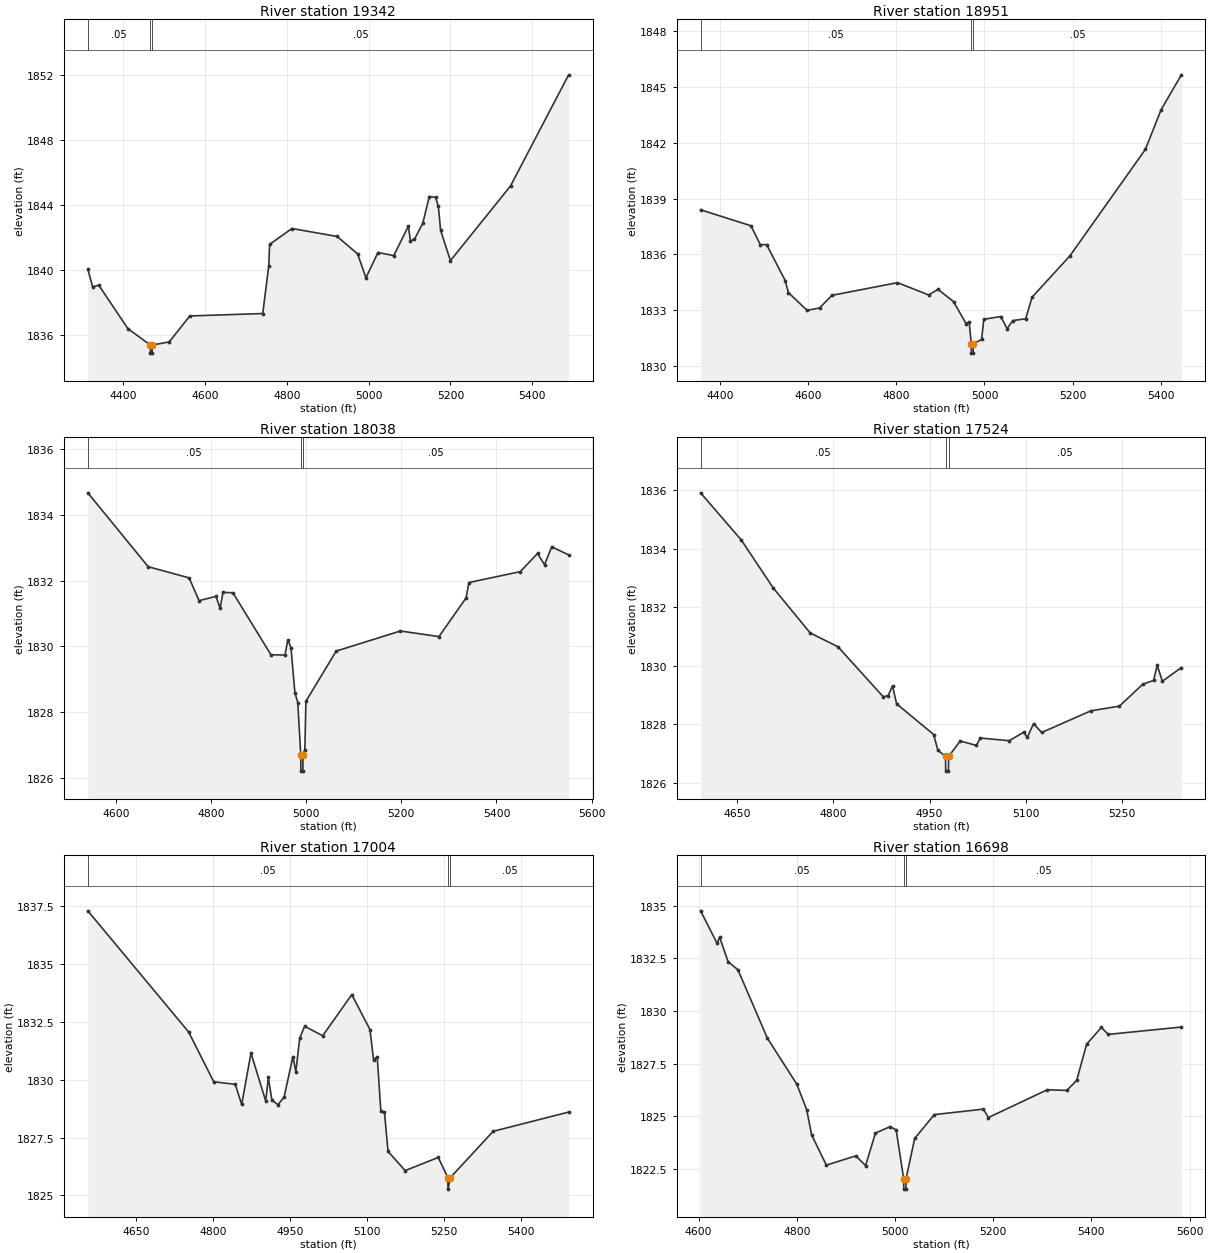
Type RM Length L Ch R = 1,19342,391,391,391
BEGIN DESCRIPTION:
Elm 02 17 19341.83
END DESCRIPTION:
XS GIS Cut Line= 6
      1619958.31      6829247.56      1620322.85      6829505.35
      1620347.59      6829746.23      1620387.96      6829780.09
      1620481.71      6829764.46      1620796.77      6829892.05
#Sta/Elev= 30
  4313.0 1840.04  4324.9 1838.96  4339.7 1839.07  4411.0 1836.39  4465.8 1835.38
  4466.2 1834.88  4470.2 1834.88  4470.5 1835.38  4512.0 1835.57  4562.5 1837.17
  4740.9 1837.32  4755.7 1840.26  4757.7 1841.58  4812.3 1842.56  4922.9 1842.07
  4973.2 1840.99  4993.4 1839.52  5022.8 1841.08  5061.5 1840.89  5097.2 1842.70
  5102.3 1841.79  5112.2 1841.90  5132.4 1842.88  5148.5 1844.53  5163.7 1844.48
  5170.6 1843.93  5176.0 1842.46  5200.1 1840.58  5347.1 1845.18  5489.3 1852.03
#Mann=3,-1,0
  4313.0    0.05       0  4465.8    0.05       0  4470.5    0.05       0
Bank Sta=4465.8,4470.5
Exp/Cntr=0.3,0.1

Type RM Length L Ch R = 1,18951,913,913,913
BEGIN DESCRIPTION:
Elm 02 17 18951.1
END DESCRIPTION:
XS GIS Cut Line= 3
      1619573.73      6829457.61      1620025.54      6829919.84
      1620383.64      6830182.89
#Sta/Elev= 30
  4356.0 1838.40  4470.3 1837.54  4491.6 1836.52  4505.7 1836.53  4548.1 1834.59
  4555.1 1833.95  4597.6 1832.99  4625.9 1833.12  4654.1 1833.80  4802.7 1834.48
  4873.5 1833.82  4894.6 1834.12  4929.9 1833.46  4958.2 1832.28  4965.3 1832.38
  4970.0 1831.19  4970.3 1830.69  4974.3 1830.69  4974.7 1831.19  4993.6 1831.43
  4998.4 1832.51  5037.1 1832.66  5051.3 1832.00  5064.2 1832.44  5093.5 1832.54
  5108.1 1833.70  5193.8 1835.92  5365.1 1841.65  5400.6 1843.78  5446.7 1845.66
#Mann=3,-1,0
  4356.0    0.05       0  4970.0    0.05       0  4974.7    0.05       0
Bank Sta=4970,4974.7
Exp/Cntr=0.3,0.1

Type RM Length L Ch R = 1,18038,514,514,514
BEGIN DESCRIPTION:
Elm 02 17 18037.57
END DESCRIPTION:
XS GIS Cut Line= 3
      1619245.75      6829760.37      1619512.65      6830134.04
      1619819.94      6830592.36
#Sta/Elev= 30
  4540.7 1834.66  4667.6 1832.42  4753.7 1832.08  4774.6 1831.39  4810.2 1831.52
  4818.8 1831.16  4824.9 1831.64  4845.8 1831.63  4925.7 1829.75  4955.2 1829.74
  4961.3 1830.20  4967.9 1829.96  4976.1 1828.60  4982.2 1828.30  4988.4 1826.72
  4988.8 1826.22  4992.9 1826.22  4993.2 1826.72  4997.0 1826.87  4999.3 1828.34
  5062.9 1829.86  5198.0 1830.47  5279.0 1830.30  5336.0 1831.47  5342.1 1831.94
  5450.1 1832.27  5486.3 1832.82  5501.1 1832.48  5516.1 1833.02  5551.7 1832.78
#Mann=3,-1,0
  4540.7    0.05       0  4988.4    0.05       0  4993.2    0.05       0
Bank Sta=4988.4,4993.2
Exp/Cntr=0.3,0.1

Type RM Length L Ch R = 1,17524,520,520,520
BEGIN DESCRIPTION:
Elm 02 17 17524.24
END DESCRIPTION:
XS GIS Cut Line= 3
      1618796.36      6830026.89      1619115.84      6830280.39
      1619421.57      6830430.67
#Sta/Elev= 30
  4593.6 1835.91  4656.9 1834.30  4706.7 1832.66  4764.3 1831.12  4807.5 1830.65
  4878.0 1828.94  4885.5 1828.98  4892.4 1829.31  4898.8 1828.70  4956.5 1827.65
  4962.9 1827.12  4974.9 1826.90  4975.2 1826.40  4979.4 1826.40  4979.8 1826.90
  4997.7 1827.43  5022.8 1827.28  5029.2 1827.53  5074.1 1827.44  5096.6 1827.73
  5102.2 1827.55  5111.9 1828.02  5124.7 1827.72  5201.1 1828.46  5245.6 1828.62
  5282.0 1829.37  5298.9 1829.50  5304.5 1830.02  5312.5 1829.47  5342.1 1829.94
#Mann=3,-1,0
  4593.6    0.05       0  4974.9    0.03       0  4979.8    0.05       0
Bank Sta=4974.9,4979.8
Exp/Cntr=0.3,0.1

Type RM Length L Ch R = 1,17004,306,306,306
BEGIN DESCRIPTION:
Elm 02 17 17004.18
END DESCRIPTION:
XS GIS Cut Line= 6
      1618462.50      6830590.97      1618726.43      6830679.52
      1618816.71      6830696.88      1618882.68      6830665.63
      1618985.11      6830563.20      1619316.73      6830457.29
#Sta/Elev= 30
  4556.2 1837.30  4752.6 1832.06  4801.4 1829.91  4843.3 1829.80  4855.8 1828.93
  4873.9 1831.15  4902.6 1829.08  4907.7 1830.10  4914.6 1829.12  4926.5 1828.92
  4938.4 1829.25  4955.6 1831.00  4961.2 1830.35  4968.9 1831.80  4978.4 1832.31
  5013.6 1831.90  5070.2 1833.68  5105.6 1832.17  5112.6 1830.86  5119.7 1830.99
  5126.8 1828.65  5133.8 1828.60  5140.8 1826.90  5174.2 1826.07  5238.6 1826.64
  5257.2 1825.77  5257.6 1825.27  5262.2 1825.77  5345.6 1827.77  5492.5 1828.60
#Mann=3,-1,0
  4556.2    0.05       0  5257.2    0.05       0  5262.2    0.05       0
Bank Sta=5257.2,5262.2
Exp/Cntr=0.3,0.1

Type RM Length L Ch R = 1,16698,162,162,162
BEGIN DESCRIPTION:
Elm 02 17 16697.75
END DESCRIPTION:
XS GIS Cut Line= 3
      1618608.86      6830862.64      1619004.69      6830866.55
      1619588.05      6830848.32
#Sta/Elev= 30
  4603.9 1834.76  4637.7 1833.21  4642.7 1833.51  4660.0 1832.34  4680.0 1831.96
  4740.0 1828.71  4800.1 1826.52  4820.1 1825.31  4830.1 1824.12  4860.1 1822.68
  4920.1 1823.12  4940.1 1822.66  4960.1 1824.20  4990.1 1824.51  5002.4 1824.35
  5017.6 1822.04  5017.9 1821.54  5022.2 1821.54  5022.6 1822.04  5040.1 1823.95
  5080.1 1825.08  5180.2 1825.34  5190.2 1824.94  5310.2 1826.26  5350.2 1826.23
  5370.2 1826.71  5390.3 1828.42  5420.3 1829.22  5434.4 1828.89  5583.4 1829.24
#Mann=3,-1,0
  4603.9    0.05       0  5017.6    0.03       0  5022.6    0.05       0
Bank Sta=5017.6,5022.6
Exp/Cntr=0.3,0.1

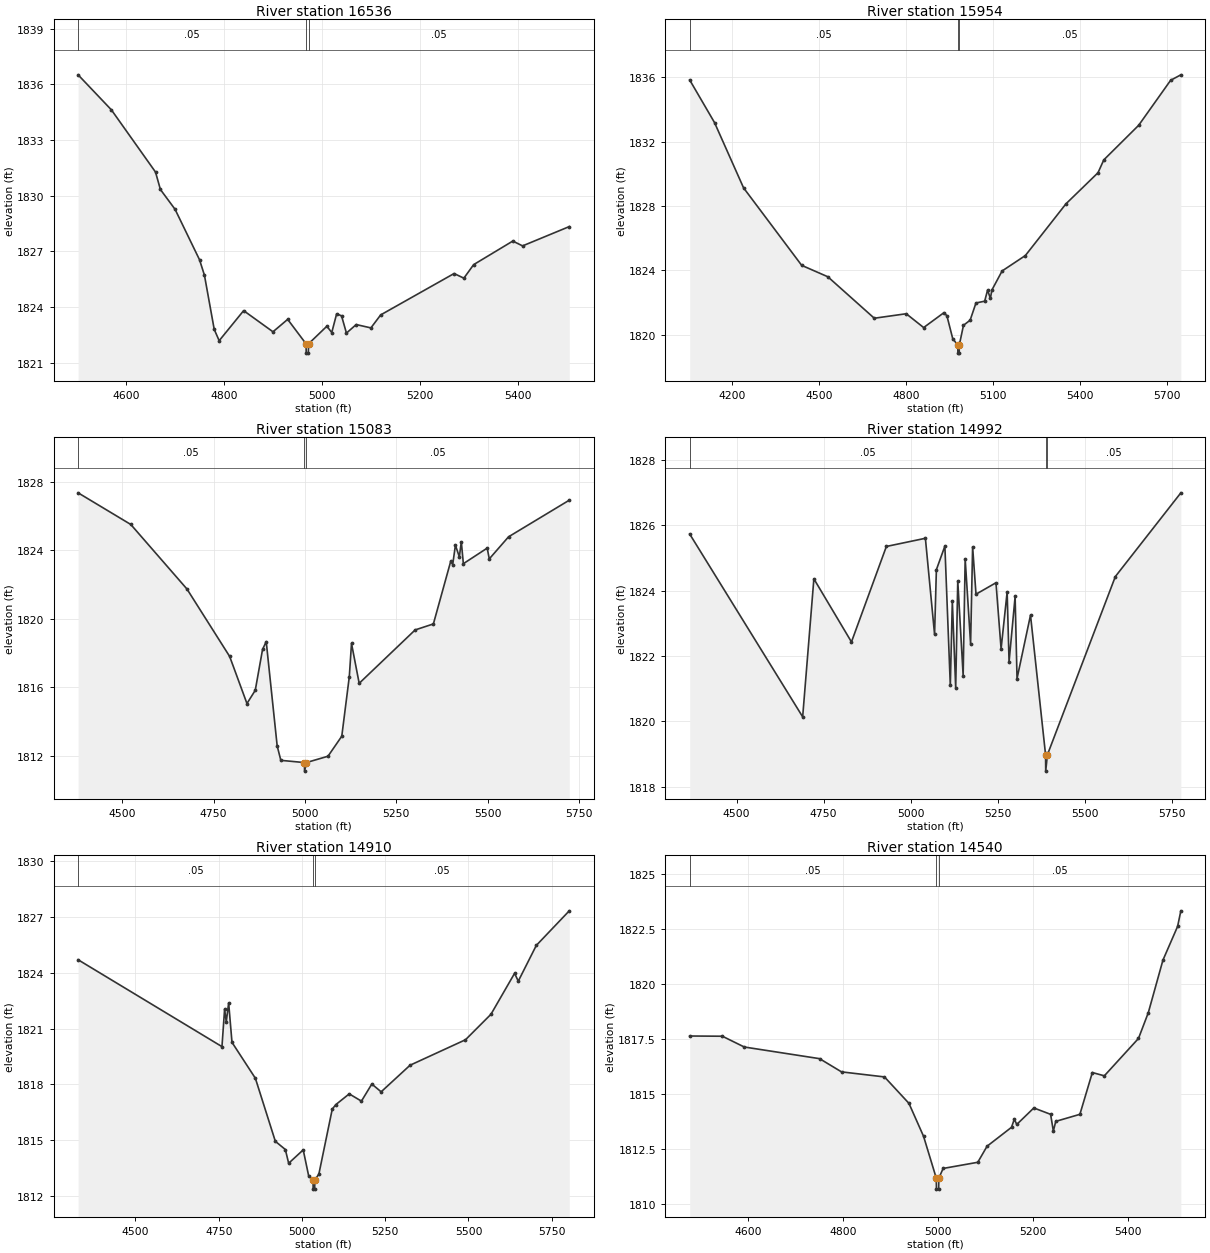
Type RM Length L Ch R = 1,16536,582,582,582
BEGIN DESCRIPTION:
Elm 02 17 16536.02
END DESCRIPTION:
XS GIS Cut Line= 3
      1618576.92      6831024.10      1619075.00      6831006.74
      1619580.36      6830999.15
#Sta/Elev= 30
  4501.5 1836.52  4569.6 1834.63  4659.7 1831.28  4669.7 1830.34  4699.7 1829.27
  4749.7 1826.55  4759.7 1825.72  4779.7 1822.80  4789.8 1822.19  4839.8 1823.81
  4899.8 1822.67  4929.8 1823.34  4967.4 1822.02  4967.7 1821.52  4972.0 1821.52
  4972.4 1822.02  5009.9 1822.97  5019.9 1822.63  5029.9 1823.64  5039.9 1823.53
  5049.9 1822.60  5069.9 1823.06  5099.9 1822.88  5119.9 1823.58  5269.9 1825.81
  5289.9 1825.56  5309.9 1826.29  5389.9 1827.56  5409.9 1827.30  5505.3 1828.34
#Mann=3,-1,0
  4501.5    0.05       0  4967.4    0.05       0  4972.4    0.05       0
Bank Sta=4967.4,4972.4
Exp/Cntr=0.3,0.1

Type RM Length L Ch R = 1,15954,871,871,871
BEGIN DESCRIPTION:
Elm 02 17 15954.32
END DESCRIPTION:
XS GIS Cut Line= 3
      1618259.52      6831466.57      1619203.95      6831485.66
      1619950.23      6831464.84
#Sta/Elev= 30
  4055.1 1835.84  4140.6 1833.19  4240.6 1829.13  4440.7 1824.31  4530.7 1823.60
  4690.7 1821.02  4800.7 1821.30  4860.7 1820.44  4930.8 1821.37  4940.8 1821.17
  4960.8 1819.75  4978.2 1819.35  4978.6 1818.85  4983.0 1818.85  4983.4 1819.35
  4997.8 1820.58  5020.8 1820.90  5040.8 1821.97  5070.8 1822.08  5080.8 1822.77
  5090.5 1822.25  5095.5 1822.77  5130.8 1823.96  5210.9 1824.92  5350.9 1828.14
  5461.0 1830.07  5481.0 1830.87  5601.0 1833.02  5711.1 1835.82  5746.3 1836.16
#Mann=3,-1,0
  4055.1    0.05       0  4978.2    0.05       0  4983.4    0.05       0
Bank Sta=4978.2,4983.4
Exp/Cntr=0.3,0.1

Type RM Length L Ch R = 1,15083,91,91,91
BEGIN DESCRIPTION:
Elm 02 17 15082.64
END DESCRIPTION:
XS GIS Cut Line= 6
      1618181.00      6832117.49      1618644.57      6832141.80
      1618804.30      6832141.80      1618873.74      6832077.56
      1619007.42      6831877.91      1619361.63      6831727.59
#Sta/Elev= 30
  4379.4 1827.36  4523.6 1825.51  4677.2 1821.74  4794.0 1817.80  4841.3 1815.05
  4864.0 1815.82  4884.0 1818.21  4894.0 1818.67  4924.0 1812.57  4934.0 1811.73
  4998.5 1811.60  4998.9 1811.10  5003.8 1811.60  5063.0 1811.97  5100.7 1813.14
  5121.3 1816.62  5127.3 1818.56  5148.3 1816.23  5301.4 1819.35  5351.3 1819.70
  5398.6 1823.35  5404.1 1823.17  5411.6 1824.30  5422.3 1823.62  5427.7 1824.50
  5433.3 1823.22  5498.5 1824.13  5504.2 1823.50  5556.9 1824.79  5723.0 1826.93
#Mann=3,-1,0
  4379.4    0.05       0  4998.5    0.05       0  5003.8    0.05       0
Bank Sta=4998.5,5003.8
Exp/Cntr=0.3,0.1

Type RM Length L Ch R = 1,14992,82,82,82
BEGIN DESCRIPTION:
Elm 02 17 14991.57
END DESCRIPTION:
XS GIS Cut Line= 6
      1618172.34      6832204.30      1618535.20      6832244.23
      1618701.87      6832244.23      1618882.42      6832209.51
      1619010.89      6831968.19      1619398.02      6831802.27
#Sta/Elev= 30
  4365.3 1825.73  4689.9 1820.14  4722.1 1824.36  4830.1 1822.43  4930.4 1825.35
  5042.5 1825.60  5068.9 1822.66  5074.1 1824.64  5098.5 1825.36  5114.1 1821.10
  5119.9 1823.68  5129.6 1821.02  5135.5 1824.30  5151.0 1821.40  5156.8 1824.97
  5172.4 1822.37  5178.2 1825.34  5187.9 1823.89  5245.3 1824.24  5260.0 1822.22
  5277.4 1823.96  5282.9 1821.82  5300.3 1823.82  5305.8 1821.31  5344.5 1823.25
  5387.8 1818.98  5388.2 1818.48  5393.1 1818.98  5588.3 1824.43  5776.5 1826.99
#Mann=3,-1,0
  4365.3    0.05       0  5387.8    0.05       0  5393.1    0.05       0
Bank Sta=5387.8,5393.1
Exp/Cntr=0.3,0.1

Type RM Length L Ch R = 1,14910,370,370,370
BEGIN DESCRIPTION:
Elm 02 17 14909.79
END DESCRIPTION:
XS GIS Cut Line= 6
      1618115.09      6832259.86      1618611.59      6832308.47
      1618788.67      6832308.47      1618941.45      6832282.42
      1619054.30      6832082.77      1619436.20      6831921.33
#Sta/Elev= 30
  4327.7 1824.70  4759.7 1820.03  4767.6 1822.04  4772.6 1821.36  4779.8 1822.38
  4789.8 1820.26  4860.0 1818.33  4920.0 1814.94  4950.0 1814.50  4960.0 1813.76
  5003.7 1814.48  5020.2 1813.07  5033.2 1812.87  5033.6 1812.37  5038.1 1812.37
  5038.5 1812.87  5050.6 1813.17  5090.9 1816.67  5101.4 1816.91  5141.9 1817.49
  5178.5 1817.10  5209.7 1818.02  5237.7 1817.60  5324.5 1819.03  5491.0 1820.40
  5567.5 1821.77  5638.4 1823.97  5649.5 1823.55  5703.6 1825.47  5802.6 1827.33
#Mann=3,-1,0
  4327.7    0.05       0  5033.2    0.05       0  5038.5    0.05       0
Bank Sta=5033.2,5038.5
Exp/Cntr=0.3,0.1

Type RM Length L Ch R = 1,14540,508,508,508
BEGIN DESCRIPTION:
Elm 02 17 14539.66
END DESCRIPTION:
XS GIS Cut Line= 3
      1618196.42      6832525.28      1618705.08      6832653.75
      1619201.66      6832778.33
#Sta/Elev= 30
  4476.0 1817.64  4545.0 1817.63  4591.2 1817.14  4750.2 1816.61  4796.4 1816.01
  4887.1 1815.78  4938.7 1814.58  4969.6 1813.08  4996.4 1811.18  4996.8 1810.68
  5001.4 1810.68  5001.8 1811.18  5010.9 1811.62  5084.0 1811.90  5103.6 1812.63
  5155.2 1813.49  5161.1 1813.86  5166.3 1813.62  5202.3 1814.37  5237.7 1814.08
  5243.5 1813.32  5248.6 1813.76  5299.5 1814.08  5325.8 1815.98  5351.1 1815.83
  5423.2 1817.53  5443.9 1818.70  5474.8 1821.09  5505.7 1822.62  5512.6 1823.33
#Mann=3,-1,0
  4476.0    0.05       0  4996.4    0.05       0  5001.8    0.05       0
Bank Sta=4996.4,5001.8
Exp/Cntr=0.3,0.1

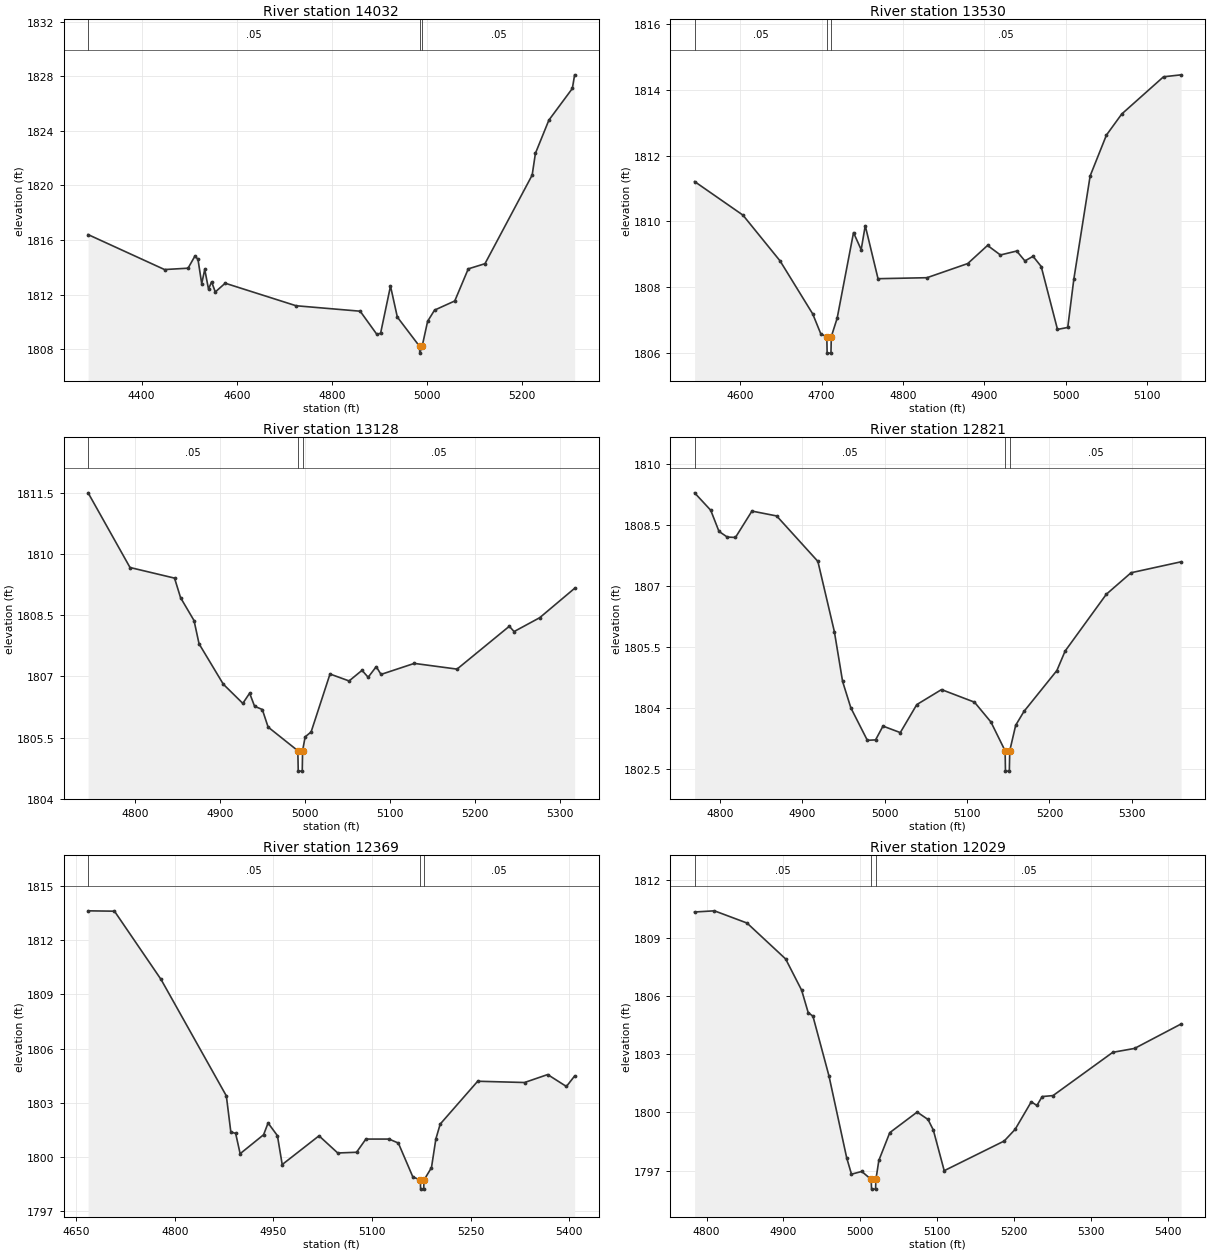
Type RM Length L Ch R = 1,14032,502,502,502
BEGIN DESCRIPTION:
Elm 02 17 14032.44
END DESCRIPTION:
XS GIS Cut Line= 3
      1618146.07      6832580.85      1618602.65      6833132.92
      1618830.03      6833339.47
#Sta/Elev= 30
  4287.3 1816.40  4448.1 1813.84  4497.6 1813.94  4511.9 1814.82  4518.4 1814.60
  4526.3 1812.81  4532.7 1813.85  4540.6 1812.41  4547.1 1812.94  4554.9 1812.20
  4575.7 1812.84  4724.8 1811.19  4859.7 1810.79  4894.9 1809.09  4902.7 1809.18
  4923.5 1812.63  4937.9 1810.36  4984.6 1808.22  4985.1 1807.72  4990.1 1808.22
  5001.6 1810.05  5016.2 1810.87  5058.7 1811.54  5087.1 1813.89  5122.3 1814.27
  5221.6 1820.76  5228.4 1822.35  5256.7 1824.78  5306.1 1827.10  5310.9 1828.10
#Mann=3,-1,0
  4287.3    0.05       0  4984.6    0.05       0  4990.1    0.05       0
Bank Sta=4984.6,4990.1
Exp/Cntr=0.3,0.1

Type RM Length L Ch R = 1,13530,402,402,402
BEGIN DESCRIPTION:
Elm 02 17 13530.39
END DESCRIPTION:
XS GIS Cut Line= 3
      1618213.93      6832833.24      1618183.55      6833288.07
      1618176.61      6833429.56
#Sta/Elev= 30
  4544.0 1811.21  4603.4 1810.19  4649.0 1808.80  4689.1 1807.19  4699.1 1806.58
  4706.4 1806.50  4706.8 1806.00  4711.5 1806.00  4711.9 1806.50  4719.1 1807.06
  4739.2 1809.66  4748.6 1809.14  4753.6 1809.87  4769.3 1808.26  4829.4 1808.29
  4879.5 1808.72  4903.8 1809.27  4919.6 1808.98  4939.6 1809.10  4949.7 1808.80
  4959.7 1808.94  4969.7 1808.63  4989.7 1806.72  5002.3 1806.78  5009.8 1808.25
  5029.8 1811.38  5049.8 1812.62  5068.6 1813.26  5119.9 1814.39  5141.5 1814.45
#Mann=3,-1,0
  4544.0    0.05       0  4706.4    0.05       0  4711.9    0.05       0
Bank Sta=4706.4,4711.9
Exp/Cntr=0.3,0.1

Type RM Length L Ch R = 1,13128,307,307,307
BEGIN DESCRIPTION:
Elm 02 17 13128.05
END DESCRIPTION:
XS GIS Cut Line= 3
      1618163.59      6832799.34      1618038.58      6833023.31
      1617897.06      6833304.63
#Sta/Elev= 30
  4745.3 1811.50  4794.5 1809.67  4846.8 1809.41  4853.9 1808.93  4869.7 1808.37
  4875.6 1807.80  4904.1 1806.81  4927.0 1806.34  4935.0 1806.59  4940.8 1806.27
  4949.9 1806.19  4956.7 1805.76  4991.6 1805.18  4992.1 1804.68  4996.8 1804.68
  4997.2 1805.18  5000.2 1805.52  5007.2 1805.64  5029.4 1807.06  5051.8 1806.89
  5067.0 1807.15  5074.2 1806.98  5083.7 1807.24  5089.3 1807.05  5128.4 1807.32
  5178.6 1807.18  5240.0 1808.23  5245.6 1808.10  5275.7 1808.44  5316.7 1809.16
#Mann=3,-1,0
  4745.3    0.05       0  4991.6    0.05       0  4997.2    0.05       0
Bank Sta=4991.6,4997.2
Exp/Cntr=0.3,0.1

Type RM Length L Ch R = 1,12821,452,452,452
BEGIN DESCRIPTION:
Elm 02 17 12820.67
END DESCRIPTION:
XS GIS Cut Line= 3
      1617745.34      6832758.43      1617743.60      6832991.08
      1617743.60      6833348.73
#Sta/Elev= 30
  4769.4 1809.30  4789.0 1808.87  4799.0 1808.35  4809.0 1808.21  4819.0 1808.20
  4839.0 1808.85  4869.0 1808.73  4919.0 1807.61  4939.0 1805.88  4949.0 1804.65
  4959.0 1804.00  4979.0 1803.20  4989.0 1803.21  4998.0 1803.55  5019.0 1803.39
  5039.0 1804.08  5069.0 1804.45  5109.0 1804.14  5129.0 1803.65  5146.2 1802.94
  5146.6 1802.44  5151.3 1802.44  5151.8 1802.94  5159.0 1803.57  5169.0 1803.91
  5209.0 1804.92  5219.0 1805.40  5269.0 1806.80  5299.0 1807.33  5359.7 1807.60
#Mann=3,-1,0
  4769.4    0.05       0  5146.2    0.05       0  5151.8    0.05       0
Bank Sta=5146.2,5151.8
Exp/Cntr=0.3,0.1

Type RM Length L Ch R = 1,12369,340,340,340
BEGIN DESCRIPTION:
Elm 02 17 12368.95
END DESCRIPTION:
XS GIS Cut Line= 3
      1617106.43      6832869.53      1617332.15      6833114.34
      1617597.59      6833423.15
#Sta/Elev= 30
  4668.2 1813.63  4708.3 1813.61  4779.2 1809.83  4878.5 1803.39  4885.3 1801.40
  4892.7 1801.31  4899.5 1800.19  4935.2 1801.24  4942.0 1801.89  4956.2 1801.19
  4963.5 1799.59  5019.5 1801.18  5048.0 1800.23  5076.6 1800.27  5090.8 1801.00
  5126.0 1801.00  5140.2 1800.78  5162.2 1798.91  5173.6 1798.73  5174.1 1798.23
  5178.8 1798.23  5179.2 1798.73  5190.6 1799.42  5197.3 1801.01  5203.9 1801.83
  5260.9 1804.20  5332.2 1804.13  5367.4 1804.57  5395.9 1803.91  5408.4 1804.49
#Mann=3,-1,0
  4668.2    0.05       0  5173.6    0.05       0  5179.2    0.05       0
Bank Sta=5173.6,5179.2
Exp/Cntr=0.3,0.1

Type RM Length L Ch R = 1,12029,840,840,840
BEGIN DESCRIPTION:
Elm 02 17 12029.24
END DESCRIPTION:
XS GIS Cut Line= 3
      1616924.18      6833213.31      1617099.51      6833341.77
      1617400.82      6833627.50
#Sta/Elev= 30
  4784.5 1810.33  4810.3 1810.39  4852.7 1809.76  4902.9 1807.91  4923.7 1806.30
  4932.2 1805.15  4938.4 1804.96  4959.2 1801.89  4982.3 1797.66  4988.5 1796.82
  5001.9 1796.96  5014.1 1796.55  5014.6 1796.05  5019.8 1796.05  5020.3 1796.55
  5024.1 1797.53  5038.3 1798.96  5073.9 1800.02  5088.0 1799.64  5094.9 1799.10
  5109.1 1797.00  5187.1 1798.53  5201.3 1799.13  5222.3 1800.55  5229.6 1800.36
  5236.5 1800.82  5250.6 1800.87  5328.3 1803.10  5356.6 1803.30  5417.1 1804.56
#Mann=3,-1,0
  4784.5    0.05       0  5014.1    0.05       0  5020.3    0.05       0
Bank Sta=5014.1,5020.3
Exp/Cntr=0.3,0.1

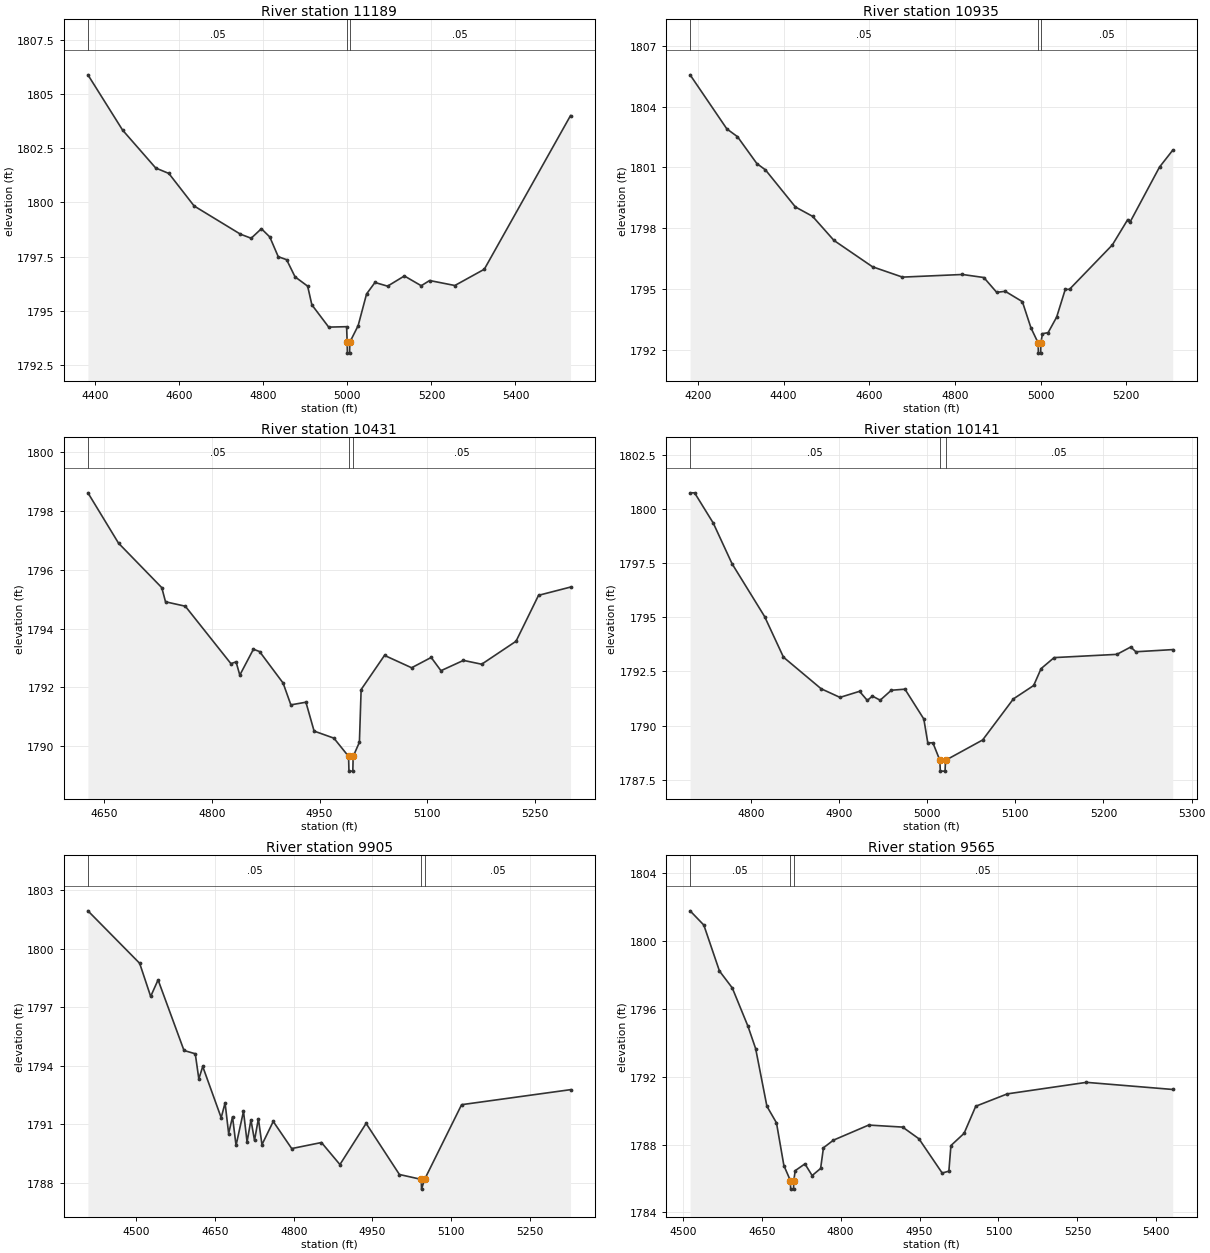
Type RM Length L Ch R = 1,11189,254,254,254
BEGIN DESCRIPTION:
Elm 02 17 11189.09
END DESCRIPTION:
XS GIS Cut Line= 3
      1616907.38      6833495.58      1616879.60      6834117.06
      1616900.43      6834643.05
#Sta/Elev= 30
  4382.5 1805.89  4465.0 1803.34  4543.9 1801.59  4575.1 1801.34  4635.2 1799.84
  4745.3 1798.54  4771.0 1798.35  4795.3 1798.79  4815.3 1798.41  4835.4 1797.50
  4855.4 1797.36  4875.4 1796.57  4905.4 1796.14  4915.4 1795.28  4955.5 1794.25
  4998.1 1794.27  4999.5 1793.55  5000.0 1793.05  5005.2 1793.05  5005.7 1793.55
  5025.6 1794.32  5045.6 1795.78  5065.6 1796.31  5095.6 1796.14  5135.6 1796.61
  5175.7 1796.16  5195.7 1796.40  5255.7 1796.17  5325.8 1796.92  5531.0 1804.01
#Mann=3,-1,0
  4382.5    0.05       0  4999.5    0.03       0  5005.7    0.05       0
Bank Sta=4999.5,5005.7
Exp/Cntr=0.3,0.1

Type RM Length L Ch R = 1,10935,504,504,504
BEGIN DESCRIPTION:
Elm 02 17 10935.17
END DESCRIPTION:
XS GIS Cut Line= 3
      1616718.14      6833492.07      1616732.03      6834316.71
      1616744.18      6834618.81
#Sta/Elev= 30
  4181.6 1805.57  4267.5 1802.90  4292.2 1802.52  4337.6 1801.19  4357.6 1800.88
  4427.6 1799.05  4467.6 1798.59  4517.6 1797.40  4607.6 1796.10  4677.6 1795.59
  4817.6 1795.72  4867.6 1795.57  4897.6 1794.84  4917.6 1794.89  4957.6 1794.38
  4977.6 1793.09  4994.5 1792.34  4995.0 1791.84  5000.3 1791.84  5000.8 1792.34
  5004.5 1792.80  5017.7 1792.85  5037.7 1793.62  5057.7 1794.98  5067.7 1794.99
  5167.8 1797.18  5203.7 1798.43  5208.7 1798.29  5277.9 1801.02  5308.7 1801.85
#Mann=3,-1,0
  4181.6    0.05       0  4994.5    0.05       0  5000.8    0.05       0
Bank Sta=4994.5,5000.8
Exp/Cntr=0.3,0.1

Type RM Length L Ch R = 1,10431,290,290,290
BEGIN DESCRIPTION:
Elm 02 17 10430.74
END DESCRIPTION:
XS GIS Cut Line= 3
      1616590.98      6833707.33      1616480.29      6834069.35
      1616393.06      6834350.56
#Sta/Elev= 30
  4626.9 1798.61  4669.6 1796.90  4729.9 1795.39  4735.1 1794.91  4762.7 1794.76
  4826.3 1792.81  4833.5 1792.87  4838.7 1792.42  4857.7 1793.30  4866.3 1793.22
  4899.1 1792.15  4909.9 1791.41  4930.9 1791.50  4942.3 1790.52  4969.9 1790.28
  4990.4 1789.66  4990.9 1789.16  4996.3 1789.16  4996.8 1789.66  5005.5 1790.14
  5007.9 1791.93  5040.5 1793.09  5078.3 1792.67  5105.6 1793.02  5119.2 1792.57
  5150.6 1792.92  5176.0 1792.79  5223.9 1793.57  5255.3 1795.13  5299.9 1795.41
#Mann=3,-1,0
  4626.9    0.05       0  4990.4    0.05       0  4996.8    0.05       0
Bank Sta=4990.4,4996.8
Exp/Cntr=0.3,0.1

Type RM Length L Ch R = 1,10141,236,236,236
BEGIN DESCRIPTION:
Elm 02 17 10141.45
END DESCRIPTION:
XS GIS Cut Line= 3
      1616445.28      6833613.37      1616305.33      6833845.55
      1616166.04      6834084.17
#Sta/Elev= 30
  4731.1 1800.76  4736.2 1800.76  4757.4 1799.36  4778.7 1797.48  4815.6 1795.04
  4837.0 1793.16  4879.7 1791.70  4901.1 1791.30  4923.3 1791.58  4932.1 1791.16
  4937.9 1791.36  4946.7 1791.17  4959.3 1791.63  4974.8 1791.68  4996.2 1790.30
  5000.7 1789.20  5006.5 1789.20  5014.4 1788.39  5014.9 1787.89  5020.3 1787.89
  5020.8 1788.39  5062.9 1789.33  5097.8 1791.23  5120.8 1791.85  5129.2 1792.63
  5144.0 1793.14  5215.2 1793.29  5230.9 1793.63  5236.7 1793.41  5278.5 1793.51
#Mann=3,-1,0
  4731.1    0.05       0  5014.4    0.05       0  5020.8    0.05       0
Bank Sta=5014.4,5020.8
Exp/Cntr=0.3,0.1

Type RM Length L Ch R = 1,9905,340,340,340
BEGIN DESCRIPTION:
Elm 02 17 9904.66
END DESCRIPTION:
XS GIS Cut Line= 3
      1616500.85      6833304.91      1616098.30      6833743.26
      1615959.18      6834036.60
#Sta/Elev= 30
  4407.7 1801.95  4506.3 1799.26  4527.3 1797.56  4541.4 1798.41  4590.8 1794.79
  4612.3 1794.62  4619.1 1793.33  4626.5 1793.97  4661.7 1791.34  4669.1 1792.10
  4675.9 1790.53  4683.3 1791.39  4690.0 1789.92  4704.2 1791.67  4711.0 1790.10
  4718.4 1791.23  4725.2 1790.18  4732.6 1791.29  4739.4 1789.96  4760.9 1791.15
  4796.1 1789.76  4852.8 1790.07  4888.0 1788.94  4937.9 1791.05  5001.4 1788.43
  5043.0 1788.18  5043.5 1787.68  5049.4 1788.18  5119.9 1792.01  5327.5 1792.78
#Mann=3,-1,0
  4407.7    0.05       0  5043.0    0.05       0  5049.4    0.05       0
Bank Sta=5043,5049.4
Exp/Cntr=0.3,0.1

Type RM Length L Ch R = 1,9565,479,479,479
BEGIN DESCRIPTION:
Elm 02 17 9565.18
END DESCRIPTION:
XS GIS Cut Line= 3
      1615990.89      6833142.11      1615811.84      6833596.78
      1615712.19      6834013.78
#Sta/Elev= 30
  4513.8 1801.79  4539.9 1800.95  4569.6 1798.24  4594.0 1797.24  4623.8 1794.98
  4638.4 1793.66  4659.8 1790.26  4678.0 1789.28  4692.1 1786.76  4704.5 1785.87
  4705.0 1785.37  4710.4 1785.37  4710.9 1785.87  4713.6 1786.46  4732.1 1786.86
  4745.8 1786.17  4761.9 1786.59  4767.3 1787.81  4786.3 1788.26  4853.3 1789.15
  4917.8 1789.03  4948.8 1788.34  4993.0 1786.32  5005.7 1786.43  5009.6 1787.94
  5034.6 1788.66  5056.8 1790.26  5116.8 1790.99  5267.2 1791.67  5431.2 1791.25
#Mann=3,-1,0
  4513.8    0.05       0  4704.5    0.05       0  4710.9    0.05       0
Bank Sta=4704.5,4710.9
Exp/Cntr=0.3,0.1