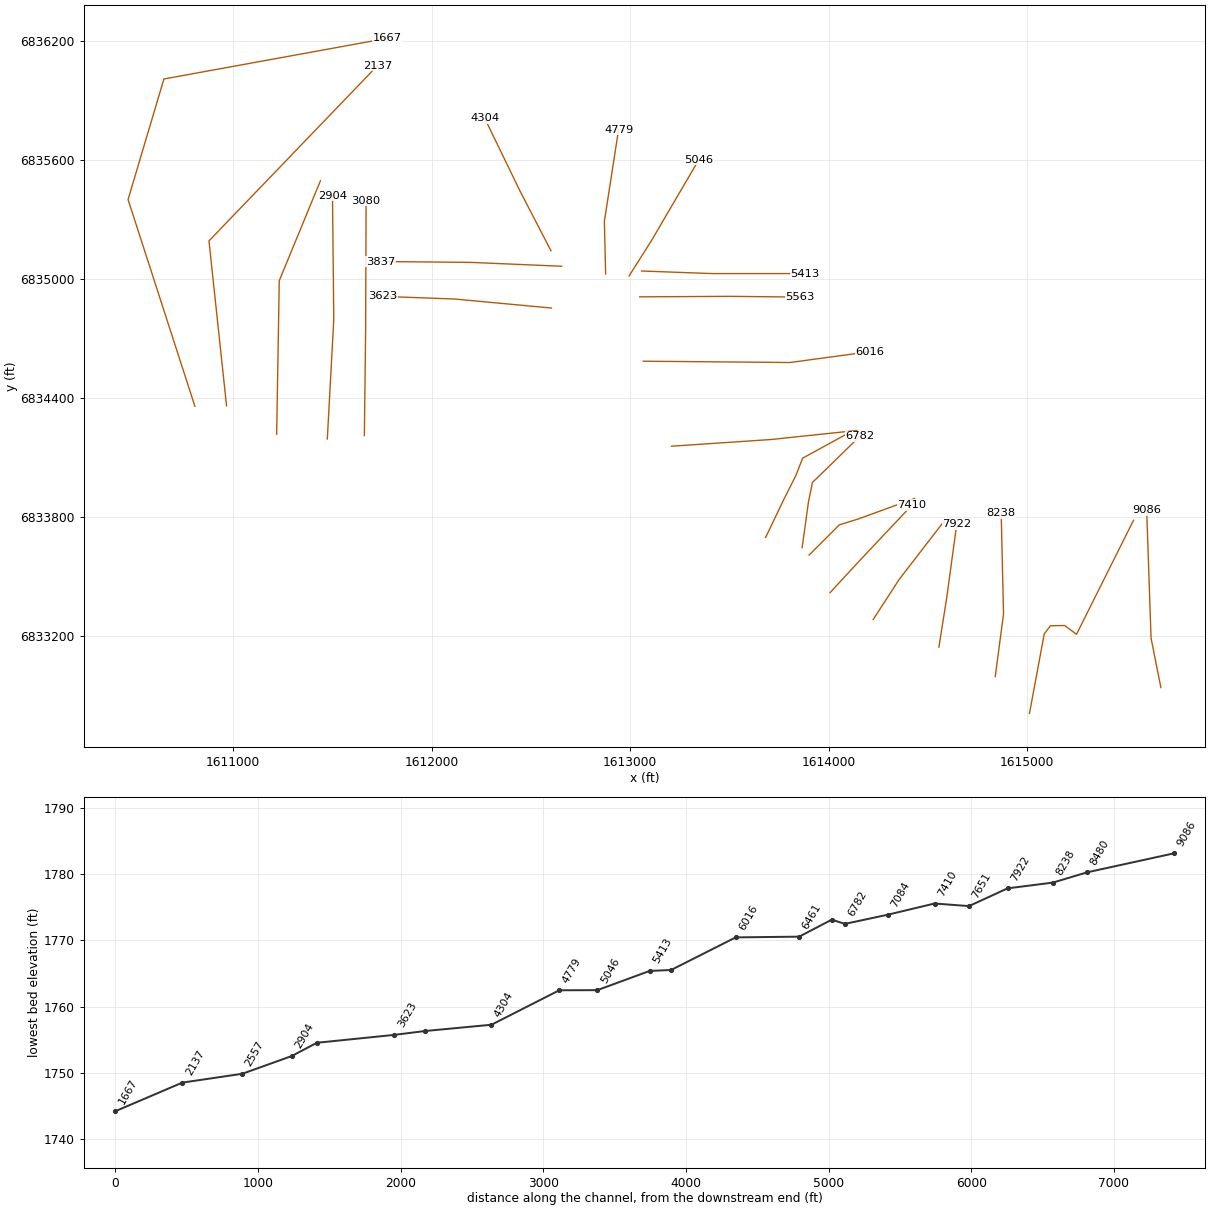
HEC-RAS study Elm 02 17.prj: Elm 02 17 Base Level Engineering

--- Elm 02 17.g01 (geometry) --- (continued)

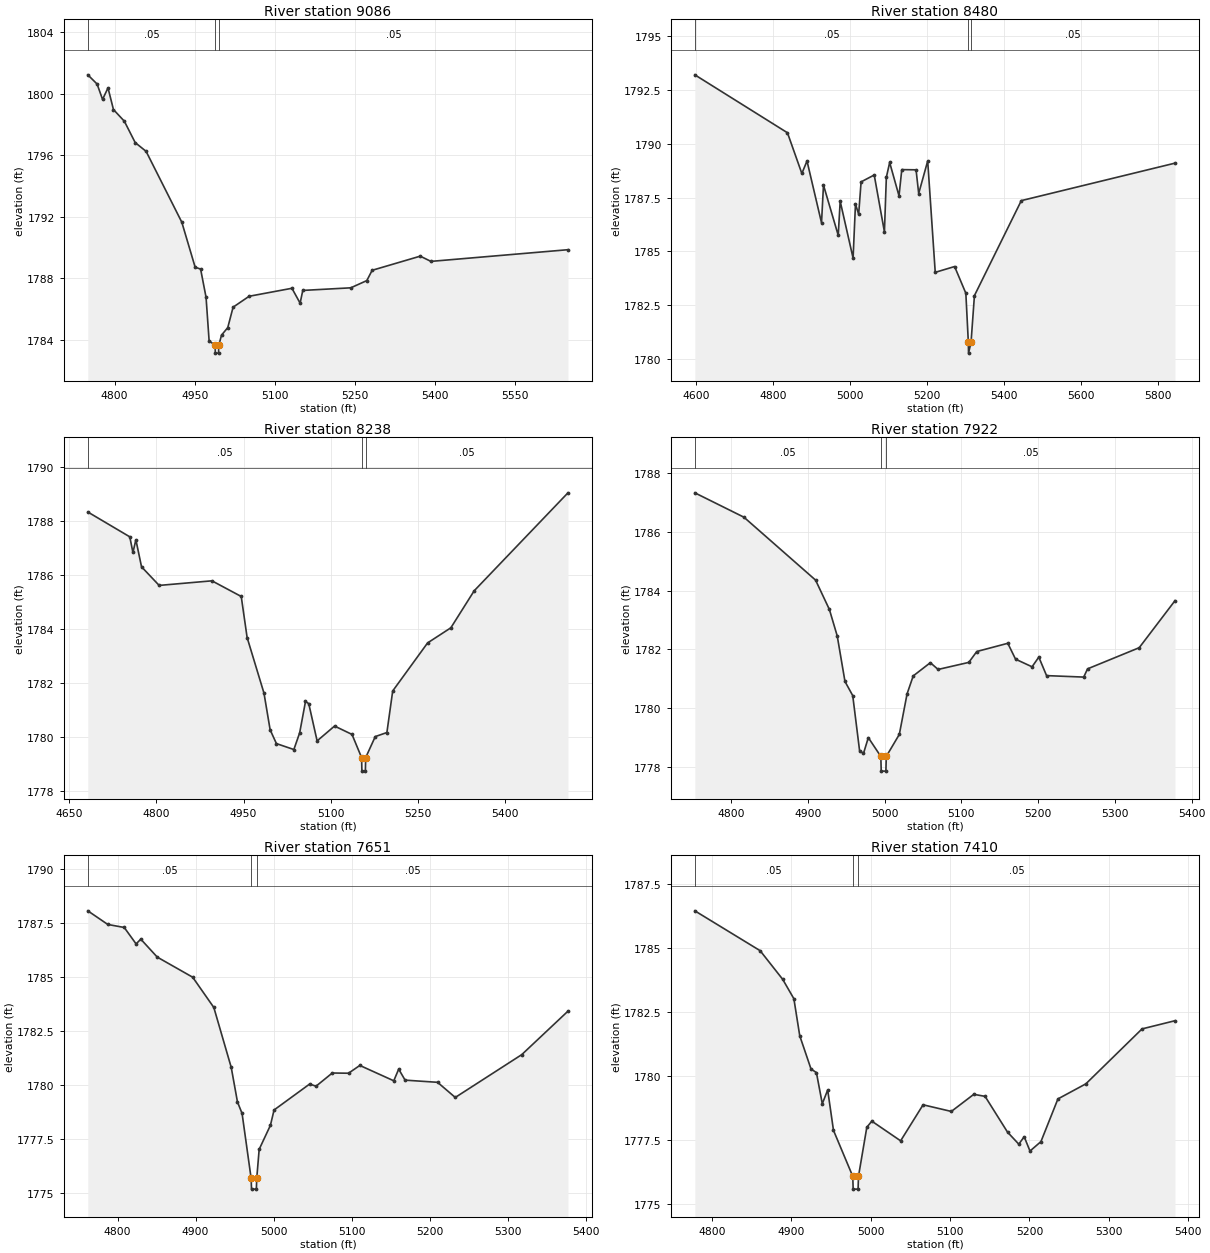
Type RM Length L Ch R = 1,9086,606,606,606
BEGIN DESCRIPTION:
Elm 02 17 9085.92
END DESCRIPTION:
XS GIS Cut Line= 3
      1615674.41      6832940.96      1615624.93      6833189.66
      1615602.84      6833834.21
#Sta/Elev= 30
  4749.8 1801.24  4767.2 1800.64  4777.4 1799.64  4787.6 1800.39  4797.8 1798.98
  4818.2 1798.22  4838.5 1796.83  4858.9 1796.26  4925.7 1791.65  4950.7 1788.72
  4960.9 1788.60  4971.1 1786.76  4976.8 1783.94  4988.0 1783.63  4988.5 1783.13
  4994.4 1783.13  4994.9 1783.63  5000.0 1784.30  5011.7 1784.79  5021.7 1786.12
  5051.7 1786.83  5131.8 1787.35  5147.1 1786.38  5152.1 1787.21  5241.9 1787.38
  5271.9 1787.85  5281.9 1788.52  5371.9 1789.44  5391.9 1789.10  5648.3 1789.86
#Mann=3,-1,0
  4749.8    0.05       0  4988.0    0.05       0  4994.9    0.05       0
Bank Sta=4988,4994.9
Exp/Cntr=0.3,0.1

Type RM Length L Ch R = 1,8480,242,242,242
BEGIN DESCRIPTION:
Elm 02 17 8479.92
END DESCRIPTION:
XS GIS Cut Line= 6
      1615012.26      6832810.92      1615086.49      6833210.69
      1615117.74      6833252.36      1615189.35      6833253.66
      1615249.25      6833209.39      1615536.54      6833783.98
#Sta/Elev= 30
  4596.2 1793.20  4836.8 1790.51  4874.2 1788.62  4887.6 1789.20  4925.3 1786.33
  4930.4 1788.08  4968.7 1785.75  4973.8 1787.33  5007.3 1784.69  5013.5 1787.20
  5021.8 1786.73  5028.1 1788.23  5062.2 1788.55  5088.7 1785.91  5093.7 1788.44
  5102.3 1789.13  5126.6 1787.58  5133.8 1788.80  5170.9 1788.79  5177.7 1787.69
  5201.1 1789.20  5220.7 1784.03  5271.0 1784.30  5300.2 1783.06  5306.7 1780.78
  5307.2 1780.28  5313.7 1780.78  5322.5 1782.95  5444.3 1787.36  5843.5 1789.10
#Mann=3,-1,0
  4596.2    0.05       0  5306.7    0.05       0  5313.7    0.05       0
Bank Sta=5306.7,5313.7
Exp/Cntr=0.3,0.1

Type RM Length L Ch R = 1,8238,316,316,316
BEGIN DESCRIPTION:
Elm 02 17 8237.84
END DESCRIPTION:
XS GIS Cut Line= 3
      1614839.78      6832996.38      1614881.45      6833311.46
      1614869.73      6833819.30
#Sta/Elev= 30
  4682.2 1788.32  4754.4 1787.40  4759.8 1786.82  4764.9 1787.29  4774.6 1786.29
  4804.9 1785.60  4895.7 1785.77  4946.1 1785.19  4956.2 1783.67  4985.2 1781.61
  4995.8 1780.25  5006.6 1779.74  5036.6 1779.52  5046.6 1780.14  5056.6 1781.30
  5062.2 1781.22  5076.6 1779.84  5106.6 1780.39  5136.6 1780.08  5153.1 1779.22
  5153.6 1778.72  5159.6 1778.72  5160.1 1779.22  5176.6 1780.00  5196.6 1780.15
  5206.6 1781.69  5266.6 1783.47  5306.6 1784.03  5346.7 1785.40  5508.0 1789.03
#Mann=3,-1,0
  4682.2    0.05       0  5153.1    0.05       0  5160.1    0.05       0
Bank Sta=5153.1,5160.1
Exp/Cntr=0.3,0.1

Type RM Length L Ch R = 1,7922,271,271,271
BEGIN DESCRIPTION:
Elm 02 17 7921.52
END DESCRIPTION:
XS GIS Cut Line= 3
      1614555.93      6833144.80      1614594.99      6833392.19
      1614645.66      6833763.79
#Sta/Elev= 30
  4752.8 1787.33  4816.8 1786.50  4910.1 1784.36  4928.1 1783.36  4938.3 1782.46
  4948.4 1780.91  4958.5 1780.43  4967.4 1778.56  4972.5 1778.46  4978.8 1779.00
  4995.1 1778.36  4995.6 1777.86  5001.7 1777.86  5002.2 1778.36  5019.2 1779.11
  5029.3 1780.49  5037.3 1781.10  5059.6 1781.55  5069.7 1781.32  5109.7 1781.56
  5120.1 1781.93  5160.5 1782.21  5170.6 1781.67  5192.1 1781.41  5200.9 1781.74
  5211.0 1781.11  5259.4 1781.06  5264.4 1781.34  5331.7 1782.06  5378.3 1783.66
#Mann=3,-1,0
  4752.8    0.05       0  4995.1    0.05       0  5002.2    0.05       0
Bank Sta=4995.1,5002.2
Exp/Cntr=0.3,0.1

Type RM Length L Ch R = 1,7651,241,241,241
BEGIN DESCRIPTION:
Elm 02 17 7651.22
END DESCRIPTION:
XS GIS Cut Line= 3
      1614224.60      6833283.74      1614355.13      6833485.09
      1614584.31      6833782.33
#Sta/Elev= 30
  4761.9 1788.05  4787.5 1787.42  4808.6 1787.28  4823.8 1786.52  4829.8 1786.74
  4850.9 1785.91  4896.3 1784.98  4923.4 1783.58  4945.7 1780.81  4953.7 1779.21
  4959.6 1778.68  4971.2 1775.68  4971.7 1775.18  4977.9 1775.18  4978.4 1775.68
  4981.5 1777.02  4995.9 1778.13  5000.6 1778.84  5046.2 1780.04  5054.4 1779.94
  5075.2 1780.55  5096.0 1780.54  5110.5 1780.90  5154.0 1780.19  5160.3 1780.73
  5168.5 1780.22  5210.1 1780.12  5232.8 1779.42  5318.0 1781.40  5377.2 1783.41
#Mann=3,-1,0
  4761.9    0.05       0  4971.2    0.05       0  4978.4    0.05       0
Bank Sta=4971.2,4978.4
Exp/Cntr=0.3,0.1

Type RM Length L Ch R = 1,7410,326,326,326
BEGIN DESCRIPTION:
Elm 02 17 7409.65
END DESCRIPTION:
XS GIS Cut Line= 3
      1614007.25      6833419.17      1614158.60      6833583.02
      1614420.58      6833860.95
#Sta/Elev= 30
  4778.4 1786.46  4860.7 1784.90  4889.1 1783.78  4903.2 1783.02  4910.6 1781.57
  4924.8 1780.27  4931.6 1780.13  4939.0 1778.91  4945.8 1779.45  4953.1 1777.87
  4977.4 1776.07  4977.9 1775.57  4984.1 1775.57  4984.6 1776.07  4995.1 1777.99
  5001.4 1778.23  5037.7 1777.46  5066.0 1778.87  5101.6 1778.61  5129.9 1779.28
  5144.1 1779.20  5172.4 1777.80  5186.6 1777.33  5193.4 1777.62  5200.7 1777.06
  5214.5 1777.43  5235.9 1779.10  5271.1 1779.69  5341.9 1781.84  5383.4 1782.16
#Mann=3,-1,0
  4778.4    0.05       0  4977.4    0.05       0  4984.6    0.05       0
Bank Sta=4977.4,4984.6
Exp/Cntr=0.3,0.1

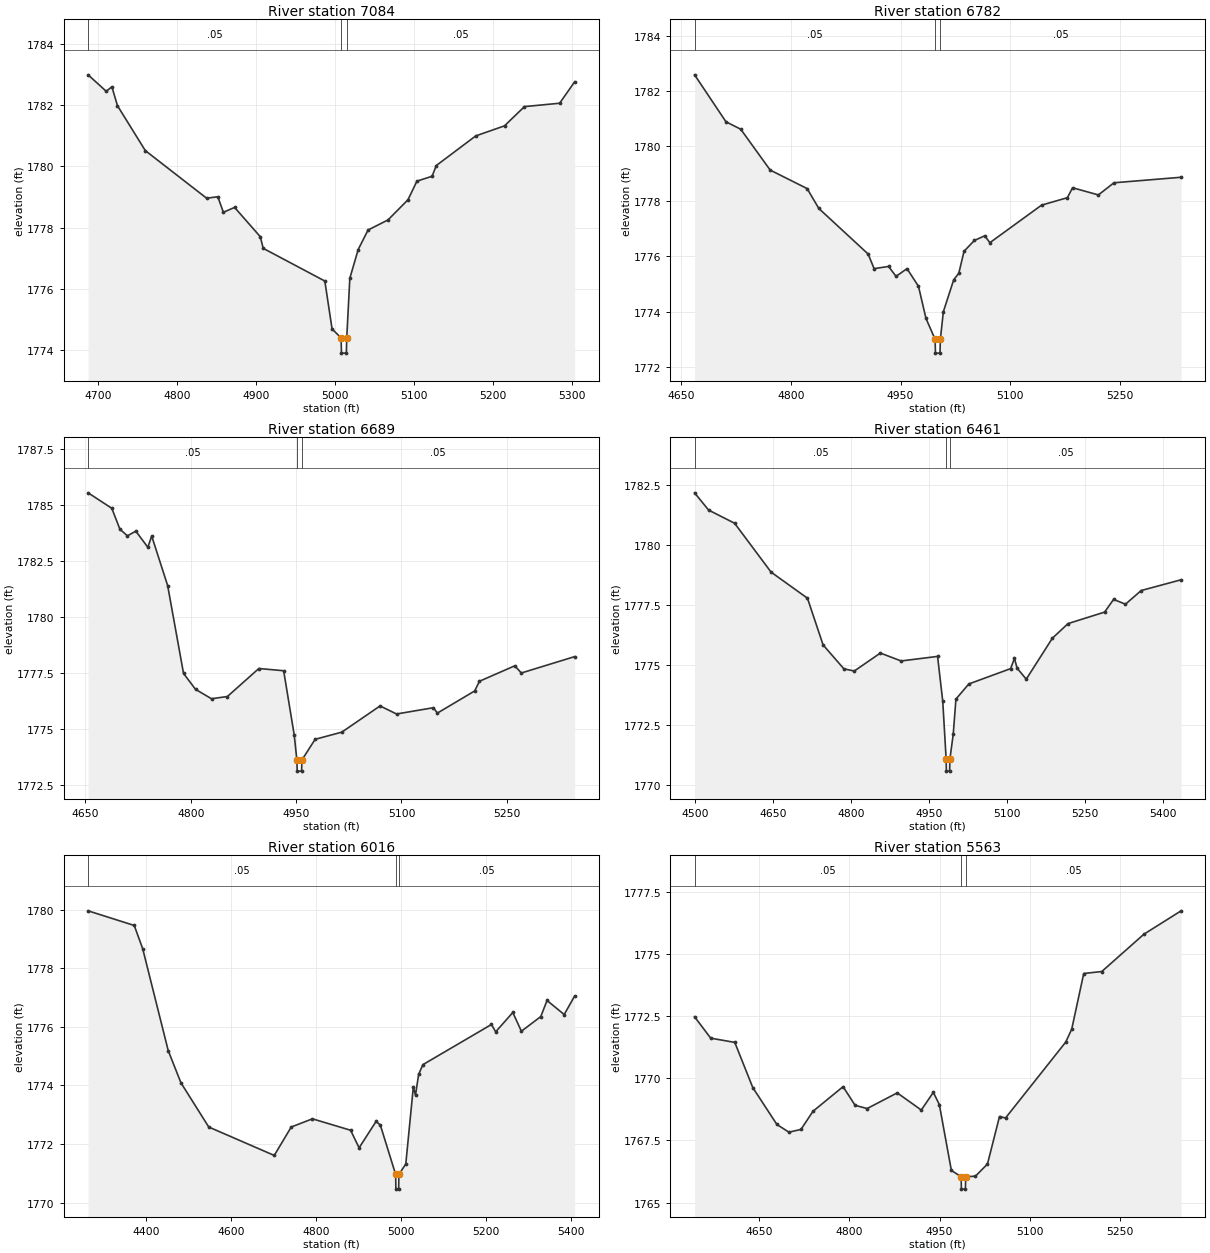
Type RM Length L Ch R = 1,7084,302,302,302
BEGIN DESCRIPTION:
Elm 02 17 7083.76
END DESCRIPTION:
XS GIS Cut Line= 4
      1613901.75      6833608.69      1614053.86      6833760.80
      1614147.61      6833789.97      1614432.88      6833893.58
#Sta/Elev= 30
  4687.1 1783.00  4710.1 1782.46  4717.2 1782.61  4724.3 1781.99  4759.6 1780.52
  4837.4 1778.96  4851.5 1779.01  4858.6 1778.50  4872.8 1778.66  4905.4 1777.70
  4909.1 1777.32  4987.2 1776.25  4996.4 1774.68  5007.8 1774.39  5008.3 1773.89
  5014.5 1773.89  5015.0 1774.39  5018.9 1776.34  5029.5 1777.28  5042.0 1777.92
  5067.3 1778.25  5092.6 1778.91  5104.0 1779.52  5123.2 1779.68  5128.5 1780.03
  5178.5 1781.00  5215.0 1781.33  5240.3 1781.96  5284.9 1782.07  5303.9 1782.77
#Mann=3,-1,0
  4687.1    0.05       0  5007.8    0.05       0  5015.0    0.05       0
Bank Sta=5007.8,5015
Exp/Cntr=0.3,0.1

Type RM Length L Ch R = 1,6782,93,93,93
BEGIN DESCRIPTION:
Elm 02 17 6782.45
END DESCRIPTION:
XS GIS Cut Line= 4
      1613866.64      6833645.53      1613898.76      6833878.17
      1613918.73      6833974.53      1614156.54      6834206.27
#Sta/Elev= 30
  4668.4 1782.58  4711.3 1780.88  4731.5 1780.61  4771.8 1779.13  4822.3 1778.46
  4838.3 1777.74  4905.7 1776.09  4913.9 1775.56  4933.7 1775.64  4943.9 1775.28
  4958.9 1775.56  4974.6 1774.92  4984.8 1773.76  4997.3 1773.00  4997.8 1772.50
  5004.0 1772.50  5004.5 1773.00  5008.6 1774.00  5022.8 1775.16  5029.7 1775.39
  5036.9 1776.19  5051.0 1776.58  5065.2 1776.75  5072.2 1776.50  5142.9 1777.86
  5178.2 1778.13  5185.3 1778.49  5220.6 1778.23  5241.9 1778.67  5333.7 1778.87
#Mann=3,-1,0
  4668.4    0.05       0  4997.3    0.05       0  5004.5    0.05       0
Bank Sta=4997.3,5004.5
Exp/Cntr=0.3,0.1

Type RM Length L Ch R = 1,6689,228,228,228
BEGIN DESCRIPTION:
Elm 02 17 6688.89
END DESCRIPTION:
XS GIS Cut Line= 5
      1613682.62      6833697.63      1613777.23      6833894.67
      1613835.39      6834010.12      1613869.25      6834096.92
      1614089.76      6834217.60
#Sta/Elev= 30
  4654.0 1785.55  4687.7 1784.86  4699.2 1783.93  4709.9 1783.63  4721.9 1783.84
  4739.0 1783.12  4744.5 1783.62  4767.2 1781.41  4789.8 1777.49  4806.9 1776.78
  4829.6 1776.36  4852.2 1776.46  4897.0 1777.71  4932.3 1777.61  4947.3 1774.75
  4951.1 1773.63  4951.6 1773.13  4957.8 1773.13  4958.3 1773.63  4977.1 1774.55
  5015.1 1774.87  5069.5 1776.04  5092.9 1775.68  5145.4 1775.96  5151.1 1775.72
  5204.2 1776.71  5210.9 1777.14  5261.2 1777.83  5270.6 1777.51  5346.4 1778.24
#Mann=3,-1,0
  4654.0    0.05       0  4951.1    0.05       0  4958.3    0.05       0
Bank Sta=4951.1,4958.3
Exp/Cntr=0.3,0.1

Type RM Length L Ch R = 1,6461,445,445,445
BEGIN DESCRIPTION:
Elm 02 17 6461.17
END DESCRIPTION:
XS GIS Cut Line= 3
      1613208.05      6834157.12      1613710.70      6834190.98
      1614141.52      6834236.40
#Sta/Elev= 30
  4498.5 1782.19  4525.5 1781.47  4575.6 1780.92  4645.8 1778.88  4715.9 1777.79
  4746.0 1775.84  4786.1 1774.84  4806.1 1774.75  4856.3 1775.50  4896.3 1775.17
  4966.5 1775.36  4976.5 1773.48  4983.0 1771.07  4983.5 1770.57  4989.7 1770.57
  4990.2 1771.07  4996.6 1772.10  5001.9 1773.58  5026.7 1774.21  5107.2 1774.85
  5114.6 1775.28  5119.6 1774.87  5137.3 1774.41  5187.6 1776.12  5217.8 1776.73
  5288.2 1777.21  5305.5 1777.74  5328.4 1777.54  5358.6 1778.11  5435.5 1778.56
#Mann=3,-1,0
  4498.5    0.05       0  4983.0    0.05       0  4990.2    0.05       0
Bank Sta=4983,4990.2
Exp/Cntr=0.3,0.1

Type RM Length L Ch R = 1,6016,453,453,453
BEGIN DESCRIPTION:
Elm 02 17 6015.54
END DESCRIPTION:
XS GIS Cut Line= 3
      1613066.18      6834585.51      1613805.75      6834579.00
      1614209.37      6834633.68
#Sta/Elev= 30
  4262.7 1779.96  4371.5 1779.46  4391.5 1778.66  4451.5 1775.19  4481.5 1774.09
  4547.1 1772.58  4701.5 1771.61  4741.5 1772.58  4791.5 1772.86  4881.5 1772.47
  4901.5 1771.87  4941.5 1772.77  4951.5 1772.65  4987.7 1770.96  4988.2 1770.46
  4994.8 1770.46  4995.3 1770.96  5011.6 1771.32  5029.4 1773.95  5034.5 1773.67
  5041.9 1774.38  5052.0 1774.71  5213.5 1776.08  5223.5 1775.83  5263.9 1776.49
  5284.1 1775.85  5329.8 1776.35  5344.6 1776.90  5385.0 1776.42  5409.6 1777.05
#Mann=3,-1,0
  4262.7    0.05       0  4987.7    0.05       0  4995.3    0.05       0
Bank Sta=4987.7,4995.3
Exp/Cntr=0.3,0.1

Type RM Length L Ch R = 1,5563,150,150,150
BEGIN DESCRIPTION:
Elm 02 17 5562.87
END DESCRIPTION:
XS GIS Cut Line= 3
      1613048.25      6834909.86      1613505.23      6834912.46
      1613856.82      6834908.56
#Sta/Elev= 30
  4542.8 1772.47  4569.6 1771.61  4609.6 1771.44  4639.6 1769.62  4679.6 1768.14
  4699.6 1767.83  4719.6 1767.94  4739.6 1768.67  4789.6 1769.66  4809.6 1768.91
  4829.6 1768.78  4879.6 1769.41  4919.6 1768.72  4939.6 1769.43  4949.6 1768.94
  4969.6 1766.29  4985.8 1766.04  4986.3 1765.54  4992.9 1765.54  4993.4 1766.04
  5009.6 1766.06  5029.6 1766.55  5049.6 1768.46  5059.6 1768.40  5159.6 1771.45
  5169.6 1771.97  5189.6 1774.21  5219.6 1774.29  5289.6 1775.79  5351.4 1776.73
#Mann=3,-1,0
  4542.8    0.05       0  4985.8    0.05       0  4993.4    0.05       0
Bank Sta=4985.8,4993.4
Exp/Cntr=0.3,0.1

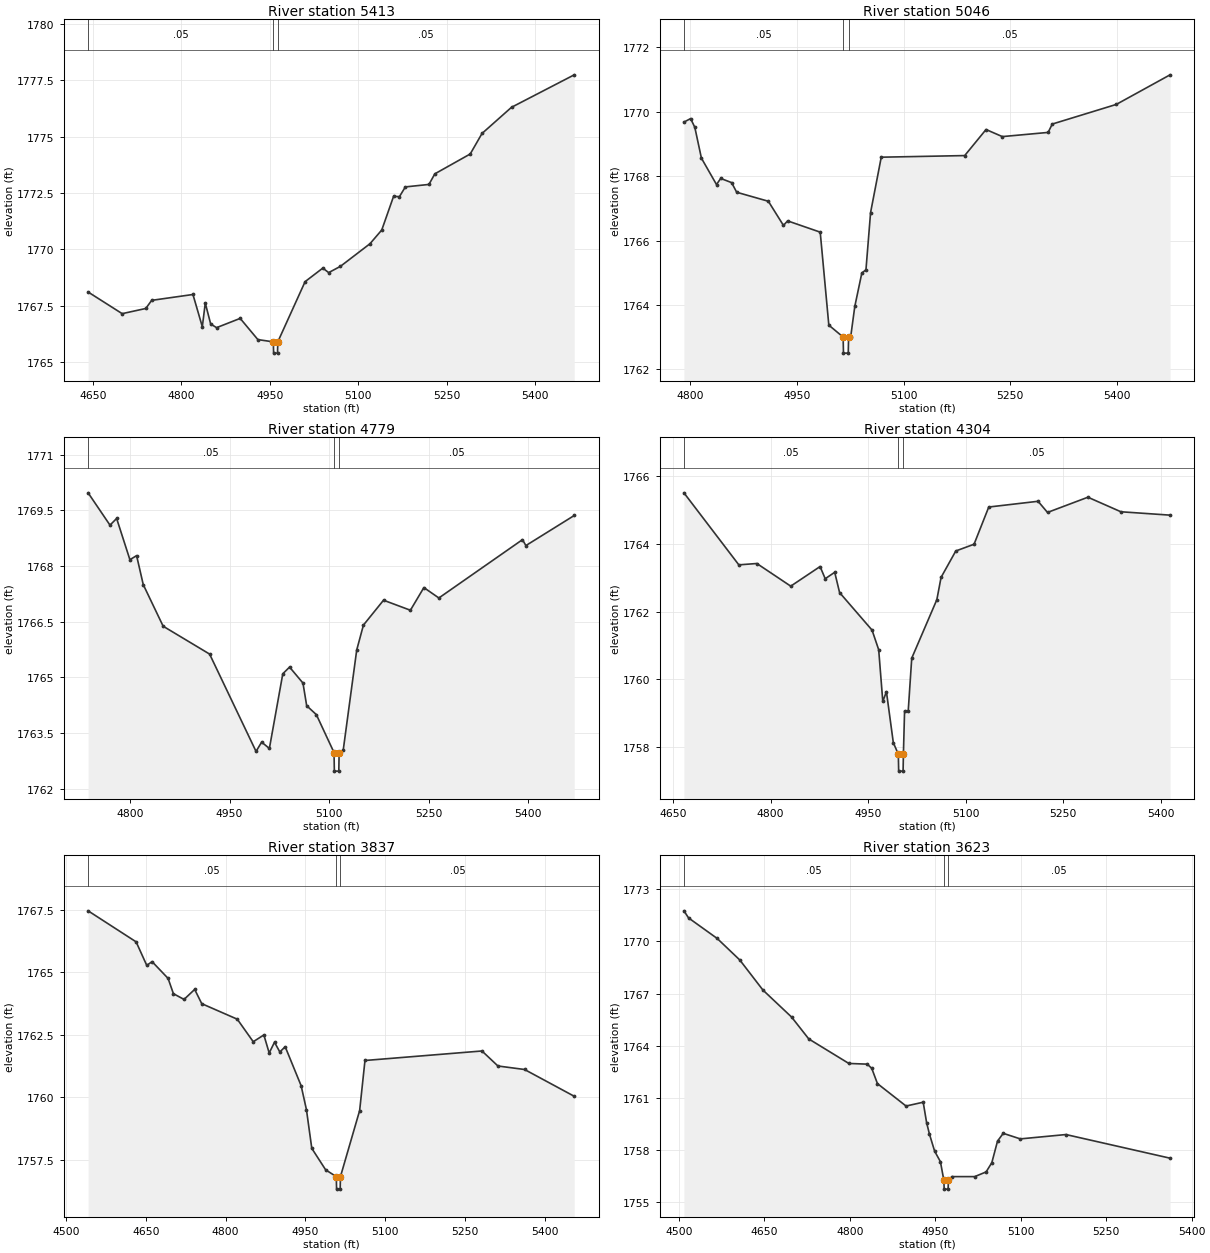
Type RM Length L Ch R = 1,5413,367,367,367
BEGIN DESCRIPTION:
Elm 02 17 5413.46
END DESCRIPTION:
XS GIS Cut Line= 3
      1613057.28      6835040.07      1613415.39      6835027.05
      1613881.44      6835027.05
#Sta/Elev= 30
  4641.8 1768.11  4699.6 1767.15  4739.6 1767.38  4749.6 1767.74  4819.6 1768.00
  4835.5 1766.57  4840.5 1767.62  4849.7 1766.69  4859.7 1766.53  4899.7 1766.94
  4929.7 1766.00  4955.9 1765.90  4956.4 1765.40  4963.0 1765.40  4963.5 1765.90
  5009.8 1768.57  5039.8 1769.17  5049.8 1768.97  5069.8 1769.25  5119.8 1770.25
  5139.8 1770.86  5159.8 1772.35  5169.8 1772.34  5179.8 1772.77  5219.8 1772.88
  5229.8 1773.35  5289.8 1774.23  5309.8 1775.14  5359.8 1776.30  5466.2 1777.74
#Mann=3,-1,0
  4641.8    0.05       0  4955.9    0.05       0  4963.5    0.05       0
Bank Sta=4955.9,4963.5
Exp/Cntr=0.3,0.1

Type RM Length L Ch R = 1,5046,267,267,267
BEGIN DESCRIPTION:
Elm 02 17 5143.66
END DESCRIPTION:
XS GIS Cut Line= 3
      1612994.82      6835015.34      1613106.58      6835191.83
      1613346.38      6835601.27
#Sta/Elev= 30
  4791.1 1769.68  4800.5 1769.79  4806.4 1769.52  4815.7 1768.56  4836.9 1767.74
  4842.8 1767.93  4858.1 1767.80  4865.3 1767.50  4909.8 1767.22  4931.0 1766.47
  4936.9 1766.61  4982.7 1766.26  4994.8 1763.37  5014.9 1763.00  5015.4 1762.50
  5022.1 1762.50  5022.6 1763.00  5025.5 1763.00  5031.3 1763.95  5041.2 1764.99
  5047.0 1765.09  5053.5 1766.87  5068.5 1768.59  5185.8 1768.64  5215.8 1769.45
  5238.7 1769.23  5303.1 1769.36  5308.9 1769.62  5398.9 1770.23  5474.5 1771.15
#Mann=3,-1,0
  4791.1    0.05       0  5014.9    0.03       0  5022.6    0.05       0
Bank Sta=5014.9,5022.6
Exp/Cntr=0.3,0.1

Type RM Length L Ch R = 1,4779,475,475,475
BEGIN DESCRIPTION:
Elm 02 17 4778.92
END DESCRIPTION:
XS GIS Cut Line= 3
      1612876.54      6835024.97      1612870.03      6835289.70
      1612941.65      6835751.97
#Sta/Elev= 30
  4736.9 1769.97  4769.9 1769.10  4779.9 1769.28  4799.9 1768.17  4810.0 1768.28
  4820.0 1767.50  4850.0 1766.38  4920.0 1765.63  4990.0 1763.01  4998.4 1763.26
  5010.1 1763.09  5030.3 1765.10  5040.5 1765.28  5060.7 1764.85  5066.3 1764.24
  5080.9 1764.00  5107.5 1762.98  5108.0 1762.48  5114.7 1762.48  5115.2 1762.98
  5121.4 1763.05  5141.7 1765.74  5151.8 1766.41  5182.1 1767.08  5222.6 1766.81
  5242.9 1767.42  5265.5 1767.14  5391.5 1768.71  5396.6 1768.55  5469.5 1769.36
#Mann=3,-1,0
  4736.9    0.05       0  5107.5    0.05       0  5115.2    0.05       0
Bank Sta=5107.5,5115.2
Exp/Cntr=0.3,0.1

Type RM Length L Ch R = 1,4304,467,467,467
BEGIN DESCRIPTION:
Elm 02 17 4304.13
END DESCRIPTION:
XS GIS Cut Line= 3
      1612600.92      6835142.16      1612444.68      6835443.78
      1612266.75      6835810.51
#Sta/Elev= 30
  4666.8 1765.51  4751.2 1763.38  4778.9 1763.42  4831.0 1762.75  4876.1 1763.33
  4884.0 1762.97  4898.6 1763.16  4906.1 1762.56  4956.0 1761.45  4966.2 1760.87
  4972.5 1759.34  4978.1 1759.63  4988.7 1758.12  4996.4 1757.78  4996.9 1757.28
  5003.7 1757.28  5004.2 1757.78  5006.0 1759.06  5011.6 1759.06  5017.0 1760.62
  5055.6 1762.35  5062.1 1763.01  5084.7 1763.79  5112.8 1763.99  5135.4 1765.09
  5211.2 1765.26  5225.7 1764.93  5287.8 1765.38  5338.5 1764.95  5414.1 1764.85
#Mann=3,-1,0
  4666.8    0.05       0  4996.4    0.05       0  5004.2    0.05       0
Bank Sta=4996.4,5004.2
Exp/Cntr=0.3,0.1

Type RM Length L Ch R = 1,3837,214,214,214
BEGIN DESCRIPTION:
Elm 02 17 3836.75
END DESCRIPTION:
XS GIS Cut Line= 3
      1612655.22      6835064.01      1612195.12      6835083.54
      1611741.55      6835087.88
#Sta/Elev= 30
  4541.3 1767.45  4631.6 1766.21  4651.6 1765.27  4661.6 1765.42  4691.7 1764.75
  4701.7 1764.14  4721.7 1763.91  4741.7 1764.31  4755.0 1763.74  4821.8 1763.12
  4851.8 1762.22  4871.8 1762.49  4881.8 1761.77  4891.8 1762.20  4901.8 1761.81
  4911.9 1762.02  4941.9 1760.46  4951.9 1759.50  4961.9 1757.96  4988.0 1757.10
  5008.0 1756.83  5008.5 1756.33  5015.3 1756.33  5015.8 1756.83  5051.9 1759.47
  5061.9 1761.47  5281.9 1761.85  5311.9 1761.25  5362.0 1761.11  5455.4 1760.04
#Mann=3,-1,0
  4541.3    0.05       0  5008.0    0.05       0  5015.8    0.05       0
Bank Sta=5008,5015.8
Exp/Cntr=0.3,0.1

Type RM Length L Ch R = 1,3623,543,543,543
BEGIN DESCRIPTION:
Elm 02 17 3623.38
END DESCRIPTION:
XS GIS Cut Line= 3
      1612603.14      6834853.50      1612112.65      6834899.08
      1611752.39      6834912.10
#Sta/Elev= 30
  4509.0 1771.76  4517.2 1771.35  4567.4 1770.17  4607.1 1768.93  4647.7 1767.20
  4697.9 1765.65  4728.1 1764.39  4798.4 1762.98  4830.7 1762.94  4838.6 1762.70
  4848.6 1761.82  4898.8 1760.53  4928.9 1760.75  4934.9 1759.57  4939.9 1758.91
  4949.0 1757.93  4959.1 1757.33  4965.2 1756.25  4965.7 1755.75  4972.6 1755.75
  4973.1 1756.25  4979.2 1756.47  5019.3 1756.47  5039.3 1756.74  5049.3 1757.27
  5059.3 1758.51  5069.3 1758.96  5099.3 1758.64  5179.4 1758.89  5362.1 1757.53
#Mann=3,-1,0
  4509.0    0.05       0  4965.2    0.05       0  4973.1    0.05       0
Bank Sta=4965.2,4973.1
Exp/Cntr=0.3,0.1

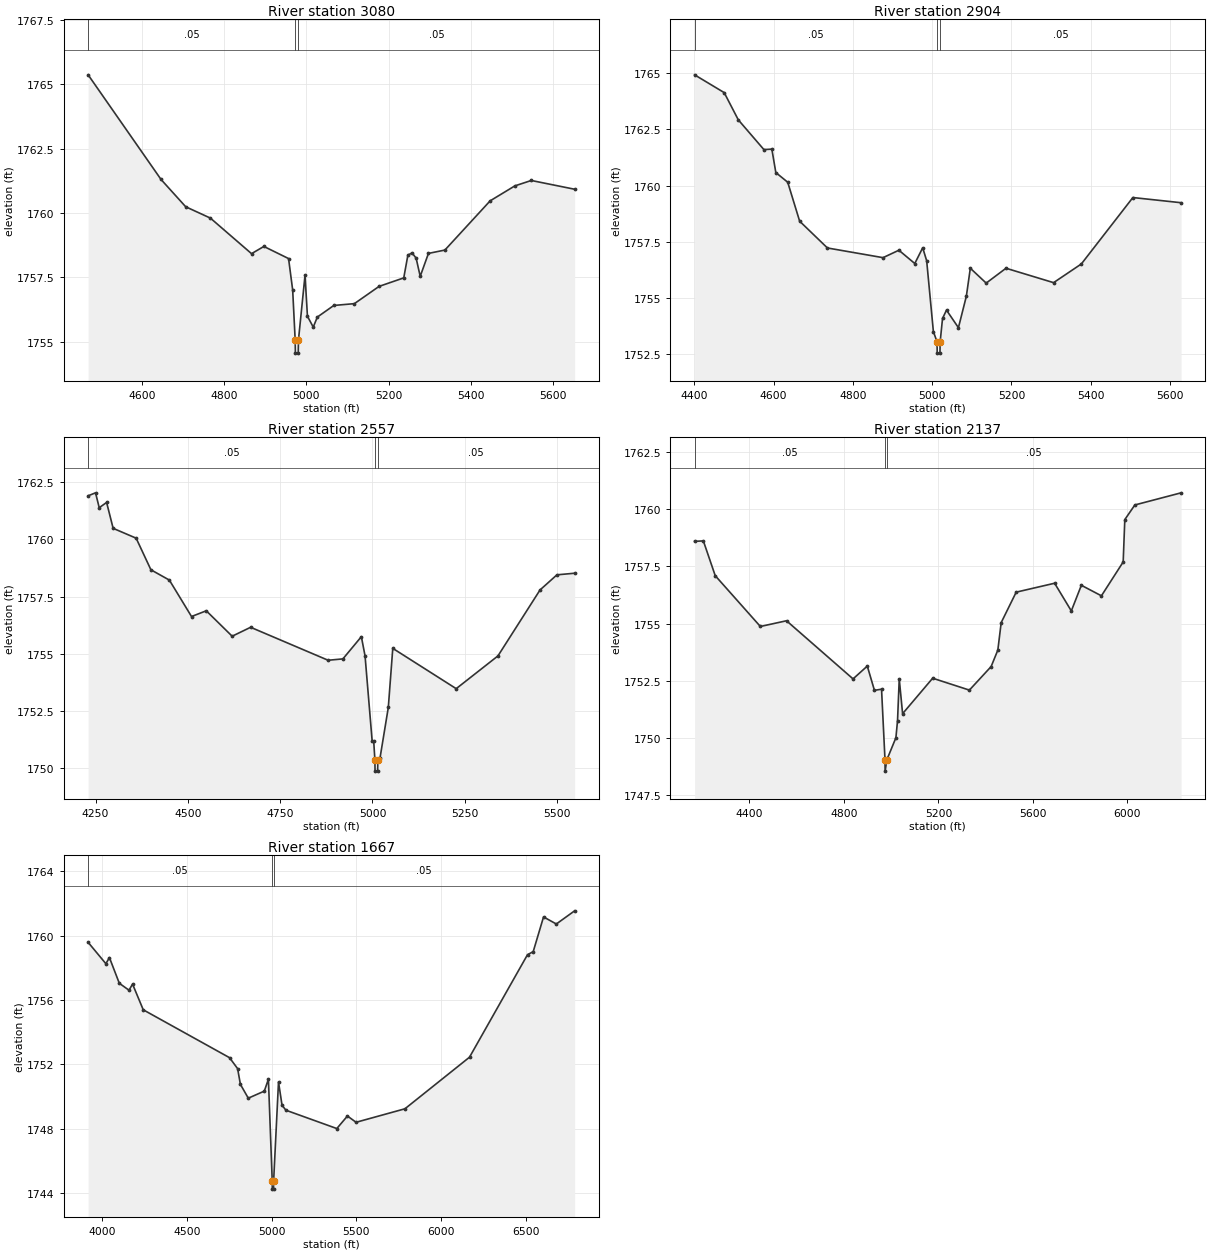
Type RM Length L Ch R = 1,3080,176,176,176
BEGIN DESCRIPTION:
Elm 02 17 3079.98
END DESCRIPTION:
XS GIS Cut Line= 3
      1611660.65      6834210.82      1611667.17      6834744.68
      1611669.33      6835393.28
#Sta/Elev= 30
  4469.6 1765.36  4646.8 1761.30  4706.8 1760.24  4766.8 1759.80  4866.8 1758.42
  4896.8 1758.70  4956.8 1758.23  4966.8 1757.01  4972.9 1755.06  4973.4 1754.56
  4980.3 1754.56  4980.8 1755.06  4996.8 1757.58  5002.7 1755.99  5016.8 1755.57
  5026.8 1755.96  5066.8 1756.41  5116.8 1756.48  5176.8 1757.15  5236.8 1757.48
  5246.8 1758.36  5256.8 1758.45  5266.8 1758.25  5276.8 1757.54  5296.8 1758.43
  5336.8 1758.56  5446.8 1760.47  5506.8 1761.05  5546.8 1761.26  5652.1 1760.92
#Mann=3,-1,0
  4469.6    0.05       0  4972.9    0.05       0  4980.8    0.05       0
Bank Sta=4972.9,4980.8
Exp/Cntr=0.3,0.1

Type RM Length L Ch R = 1,2904,347,347,347
BEGIN DESCRIPTION:
Elm 02 17 2903.95
END DESCRIPTION:
XS GIS Cut Line= 3
      1611474.02      6834193.43      1611506.58      6834796.77
      1611500.06      6835419.62
#Sta/Elev= 30
  4400.8 1764.92  4475.5 1764.13  4511.1 1762.92  4575.6 1761.60  4595.7 1761.62
  4605.7 1760.58  4635.7 1760.15  4665.8 1758.42  4735.9 1757.23  4876.1 1756.80
  4916.1 1757.13  4956.2 1756.54  4976.2 1757.24  4986.2 1756.66  5003.1 1753.52
  5012.3 1753.06  5012.8 1752.56  5019.7 1752.56  5020.2 1753.06  5026.2 1754.10
  5036.2 1754.47  5066.3 1753.69  5086.3 1755.09  5096.3 1756.33  5136.3 1755.67
  5186.3 1756.33  5306.3 1755.69  5376.3 1756.52  5506.3 1759.47  5627.9 1759.24
#Mann=3,-1,0
  4400.8    0.05       0  5012.3    0.05       0  5020.2    0.05       0
Bank Sta=5012.3,5020.2
Exp/Cntr=0.3,0.1

Type RM Length L Ch R = 1,2557,420,420,420
BEGIN DESCRIPTION:
Elm 02 17 2557.18
END DESCRIPTION:
XS GIS Cut Line= 3
      1611218.81      6834217.90      1611231.84      6834991.35
      1611439.35      6835494.58
#Sta/Elev= 30
  4229.8 1761.90  4249.9 1762.03  4259.9 1761.38  4279.9 1761.61  4297.6 1760.48
  4359.9 1760.05  4399.9 1758.67  4449.9 1758.22  4509.9 1756.63  4549.9 1756.88
  4620.0 1755.77  4670.0 1756.16  4880.0 1754.72  4920.0 1754.78  4970.0 1755.75
  4980.0 1754.91  4999.2 1751.20  5003.4 1751.20  5006.6 1750.38  5007.1 1749.88
  5014.1 1749.88  5014.6 1750.38  5020.4 1750.44  5043.0 1752.66  5055.1 1755.24
  5226.9 1753.48  5340.0 1754.91  5454.0 1757.79  5499.8 1758.45  5547.7 1758.52
#Mann=3,-1,0
  4229.8    0.05       0  5006.6    0.05       0  5014.6    0.05       0
Bank Sta=5006.6,5014.6
Exp/Cntr=0.3,0.1

Type RM Length L Ch R = 1,2137,470,470,470
BEGIN DESCRIPTION:
Elm 02 17 2137.27
END DESCRIPTION:
XS GIS Cut Line= 3
      1610966.21      6834361.12      1610877.67      6835191.88
      1611725.84      6836073.87
#Sta/Elev= 30
  4168.0 1758.59  4205.1 1758.61  4255.4 1757.09  4446.4 1754.87  4557.1 1755.12
  4838.7 1752.58  4899.0 1753.14  4929.2 1752.08  4959.3 1752.13  4973.9 1749.05
  4974.4 1748.55  4982.0 1749.05  5020.1 1750.01  5027.0 1750.76  5034.2 1752.58
  5048.4 1751.06  5175.7 1752.61  5331.1 1752.09  5423.2 1753.12  5451.5 1753.84
  5465.7 1755.04  5529.2 1756.37  5691.8 1756.76  5762.5 1755.55  5805.0 1756.67
  5889.9 1756.21  5982.0 1757.69  5988.9 1759.54  6031.4 1760.18  6227.1 1760.71
#Mann=3,-1,0
  4168.0    0.05       0  4973.9    0.05       0  4982.0    0.05       0
Bank Sta=4973.9,4982
Exp/Cntr=0.3,0.1

Type RM Length L Ch R = 1,1667,0,0,0
BEGIN DESCRIPTION:
Elm 02 17 1666.77
END DESCRIPTION:
XS GIS Cut Line= 4
      1610806.83      6834358.28      1610470.01      6835399.99
      1610650.57      6836007.63      1611775.56      6836212.49
#Sta/Elev= 30
  3917.2 1759.59  4022.0 1758.26  4043.0 1758.64  4101.4 1757.04  4158.6 1756.61
  4179.6 1756.99  4242.7 1755.39  4752.2 1752.41  4799.7 1751.73  4816.3 1750.75
  4862.8 1749.89  4957.4 1750.33  4981.6 1751.07  5004.2 1744.73  5004.7 1744.23
  5011.9 1744.23  5012.4 1744.73  5041.2 1750.90  5062.1 1749.45  5085.2 1749.14
  5385.5 1748.00  5448.1 1748.78  5499.2 1748.39  5787.6 1749.23  6168.8 1752.44
  6511.2 1758.82  6544.9 1759.01  6605.9 1761.17  6681.4 1760.73  6789.4 1761.55
#Mann=3,-1,0
  3917.2    0.05       0  5004.2    0.05       0  5012.4    0.05       0
Bank Sta=5004.2,5012.4
Exp/Cntr=0.3,0.1

Chan Stop Cuts=-1