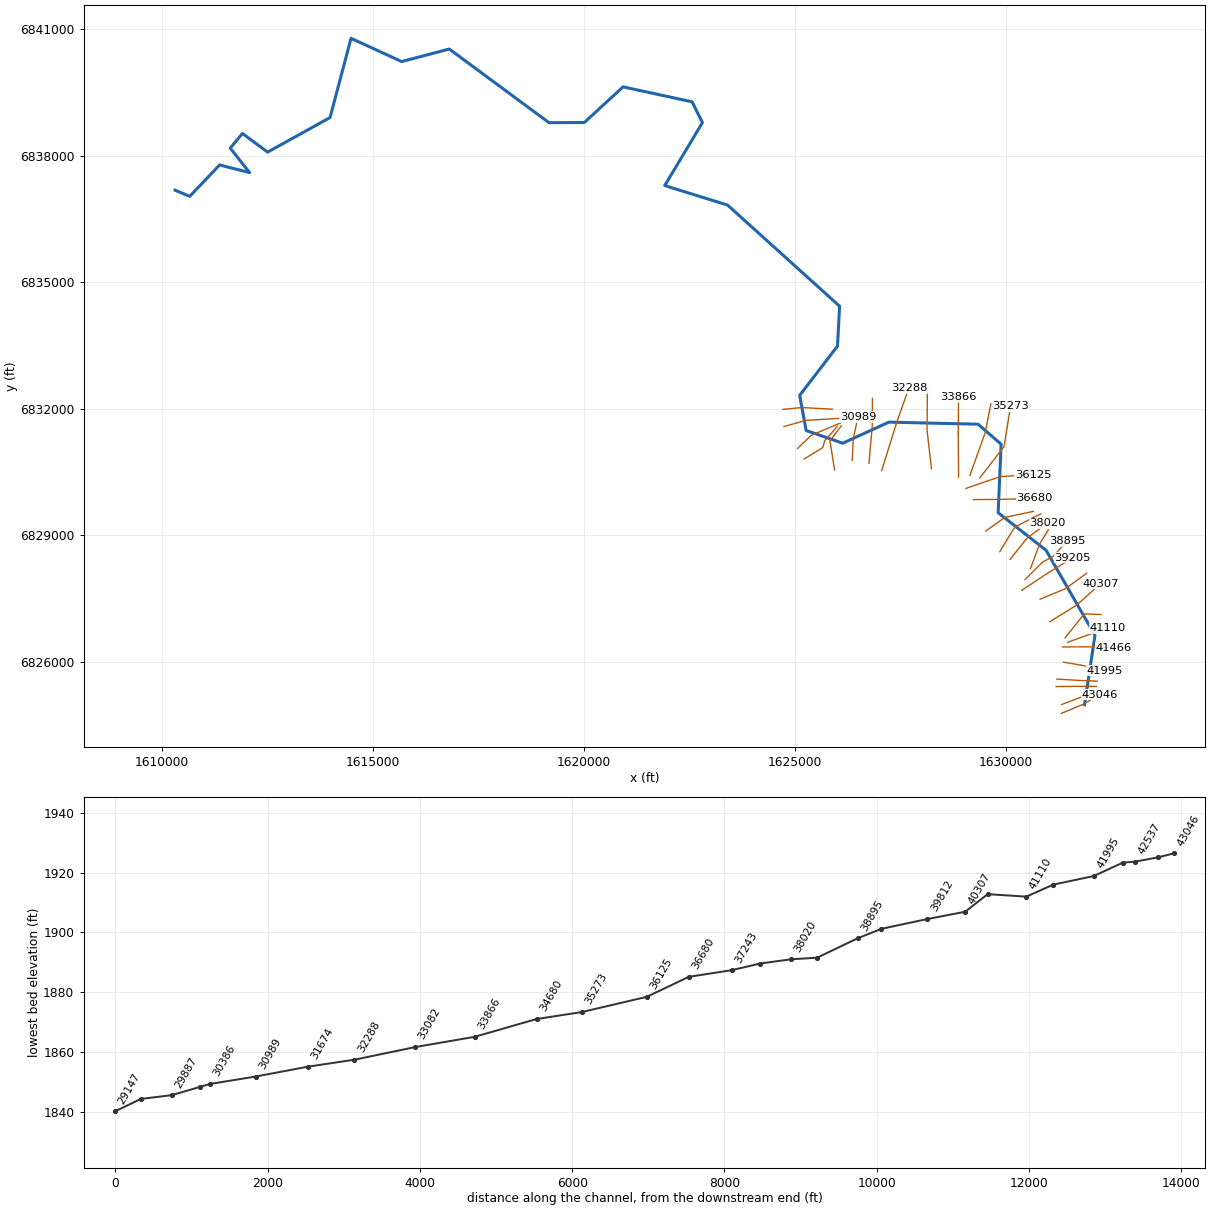
--- Elm 02 18.prj (project) ---

Proj Title=Elm 02 18 Base Level Engineering
Current Plan=p01
Default Exp/Contr=0.3,0.1
English Units
Geom File=g01
Flow File=f01
Plan File=p01
Y Axis Title=Elevation
X Axis Title(PF)=Main Channel Distance
X Axis Title(XS)=Station
BEGIN DESCRIPTION:
Elm 02 18
END DESCRIPTION:
DSS Export Rating Curves= 0
DSS Export Rating Curve Sorted= 0
DSS Export Volume Flow Curves= 0
DXF OffsetX= 0
DXF OffsetY= 0
DXF ScaleX= 1
DXF ScaleY= 10

--- Elm 02 18.p01 (plan) ---

Plan Title=Multiple Run
Short Identifier=Multiple
Geom File=g01
Flow File=f01
Subcritical Flow
K Sum by GR= 0
Std Step Tol= 0.01
Critical Tol= 0.01
Num of Std Step Trials= 20
Max Error Tol= 0.3
Flow Tol Ratio= 0.001
Split Flow NTrial= 30
Split Flow Tol= 0.02
Split Flow Ratio= 0.02
Log Output Level= 0
Friction Slope Method= 1
Unsteady Friction Slope Method= 2
Unsteady Bridges Friction Slope Method= 1
Parabolic Critical Depth
Global Vel Dist=  1 , 1 , 1
Global Log Level= 0
CheckData=True
Encroach Param= -1, 0, 0, 0
BEGIN DESCRIPTION:
Multiple Run
END DESCRIPTION:

--- Elm 02 18.f01 (steady flow) ---

Flow Title=Multiple
Program Version=4.10
Number of Profiles= 7
Profile Names=10-year,25-year,50-year,1pct_min,100-year,1pct_plu,500-year
River Rch & RM=Elm 02 18,Reach-1         ,43046
     231     320     394     301     482     663     730
River Rch & RM=Elm 02 18,Reach-1         ,40307
     325     458     569     439     703     967    1090
River Rch & RM=Elm 02 18,Reach-1         ,34680
     465     668     841     656    1050    1450    1660
River Rch & RM=Elm 02 18,Reach-1         ,32288
     556     805    1020     798    1280    1760    2040
River Rch & RM=Elm 02 18,Reach-1         ,30260
     743    1090    1380    1090    1750    2410    2830
River Rch & RM=Elm 02 18,Reach-1         ,29887
     743    1090    1380    1090    1750    2410    2830
River Rch & RM=Elm 02 18,Reach-1         ,22445
     828    1220    1550    1230    1960    2700    3190
River Rch & RM=Elm 02 18,Reach-1         ,18592
     898    1320    1690    1330    2130    2940    3470
River Rch & RM=Elm 02 18,Reach-1         ,9766
     953    1400    1790    1420    2270    3120    3690
River Rch & RM=Elm 02 18,Reach-1         ,4662
     979    1440    1840    1450    2330    3210    3790
River Rch & RM=Elm 02 18,Reach-1         ,1812
     979    1440    1840    1450    2330    3210    3790
Boundary for River Rch & Prof#=Elm 02 18,Reach-1         , 1
Up Type= 0
Dn Type= 3
Dn Slope=0.001
Boundary for River Rch & Prof#=Elm 02 18,Reach-1         , 2
Up Type= 0
Dn Type= 3
Dn Slope=0.001
Boundary for River Rch & Prof#=Elm 02 18,Reach-1         , 3
Up Type= 0
Dn Type= 3
Dn Slope=0.001
Boundary for River Rch & Prof#=Elm 02 18,Reach-1         , 4
Up Type= 0
Dn Type= 3
Dn Slope=0.001
Boundary for River Rch & Prof#=Elm 02 18,Reach-1         , 5
Up Type= 0
Dn Type= 3
Dn Slope=0.001
Boundary for River Rch & Prof#=Elm 02 18,Reach-1         , 6
Up Type= 0
Dn Type= 3
Dn Slope=0.001
Boundary for River Rch & Prof#=Elm 02 18,Reach-1         , 7
Up Type= 0
Dn Type= 3
Dn Slope=0.001
DSS Import GetInterval= 0
DSS Import GetPeak= 0
DSS Import FillOption= 0

--- Elm 02 18.g01 (geometry) ---

Geom Title=Existing Conditions

River Reach=Elm 02 18,Reach-1
Reach XY= 30
      1631855.00      6824988.00      1632102.65      6826632.48
      1630944.57      6828647.79      1629808.37      6829539.28
      1629878.52      6831165.12      1629332.35      6831638.22
      1627220.22      6831687.48      1626125.18      6831187.57
      1625258.54      6831489.46      1625105.50      6832322.78
      1626001.46      6833489.46      1626051.46      6834436.54
      1623396.66      6836834.84      1621908.37      6837296.37
      1622801.25      6838789.55      1622557.45      6839282.53
      1620920.16      6839637.62      1620003.42      6838791.82
      1619165.43      6838789.05      1616803.53      6840534.46
      1615675.21      6840237.64      1614474.96      6840788.26
      1613978.52      6838910.88      1612499.10      6838089.97
      1611902.53      6838532.55      1611612.76      6838184.95
      1612071.83      6837604.40      1611360.97      6837785.86
      1610653.53      6837041.55      1610305.00      6837188.00

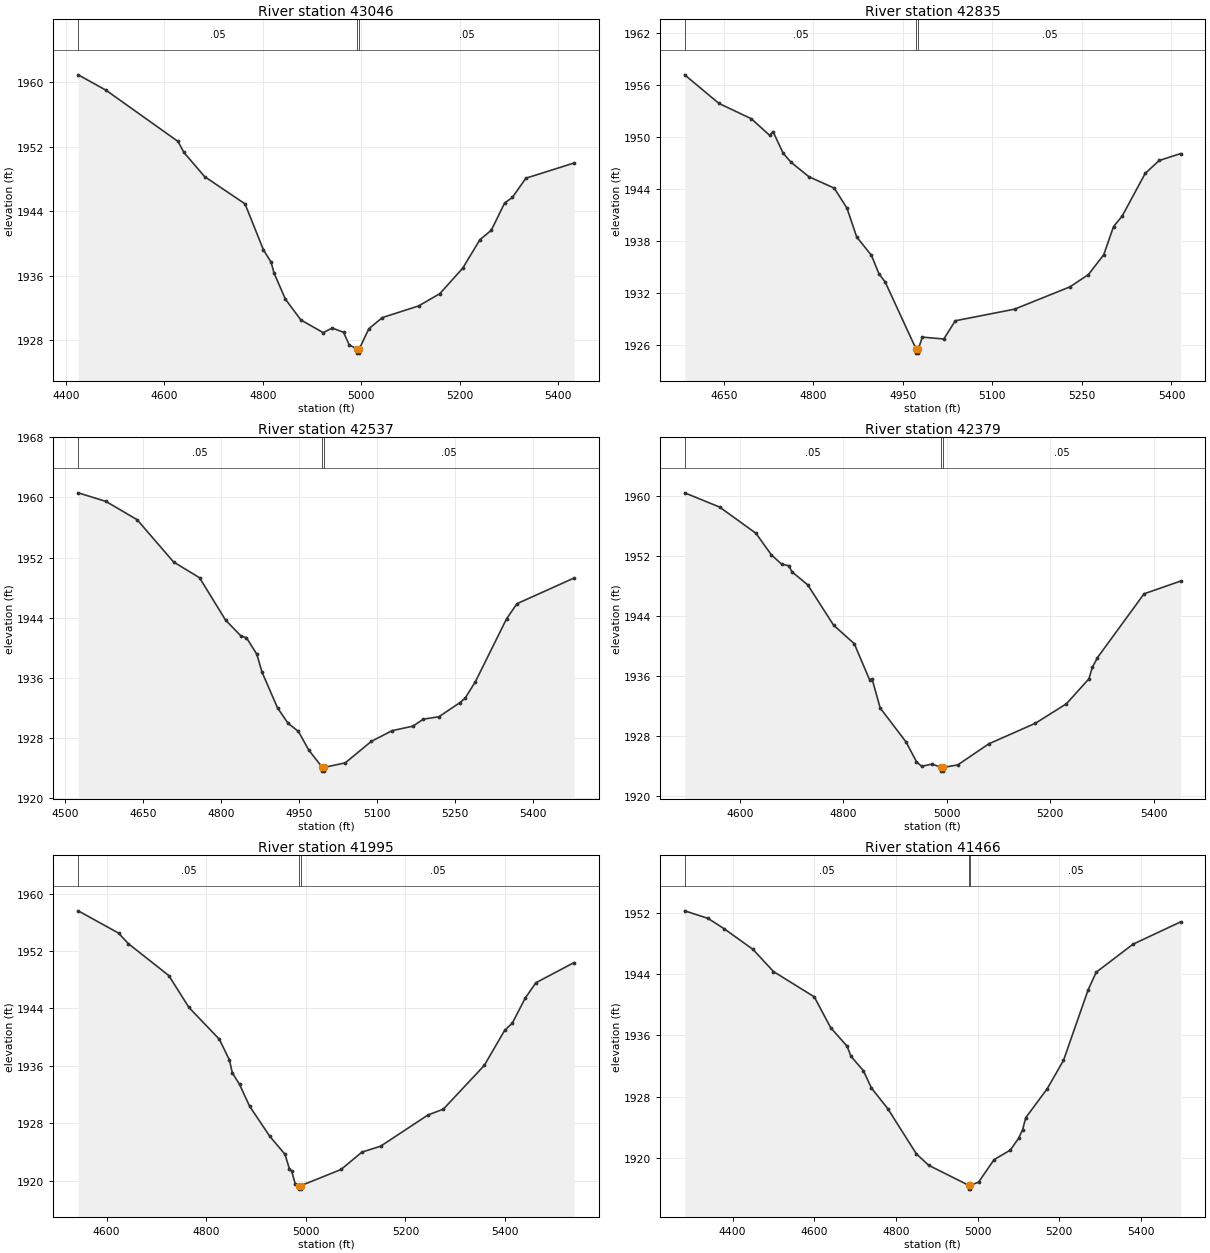
Type RM Length L Ch R = 1,43046,211,211,211
BEGIN DESCRIPTION:
Elm 02 18 42650.084
END DESCRIPTION:
XS GIS Cut Line= 3
      1631308.08      6824781.44      1631838.05      6825004.24
      1632209.14      6825226.77
#Sta/Elev= 30
  4425.1 1960.89  4481.1 1959.00  4627.9 1952.63  4639.8 1951.27  4681.9 1948.27
  4764.0 1944.89  4801.4 1939.19  4816.9 1937.67  4823.1 1936.29  4846.1 1933.07
  4877.4 1930.50  4922.8 1928.92  4941.1 1929.49  4964.1 1928.97  4975.7 1927.40
  4992.0 1926.88  4992.3 1926.38  4995.8 1926.38  4996.0 1926.88  5015.5 1929.40
  5043.1 1930.79  5116.6 1932.23  5159.7 1933.75  5206.0 1936.89  5241.3 1940.45
  5264.3 1941.61  5291.5 1945.00  5307.1 1945.68  5334.6 1948.07  5432.7 1949.96
#Mann=3,-1,0
  4425.1    0.05       0  4992.0    0.05       0  4996.0    0.05       0
Bank Sta=4992,4996
Exp/Cntr=0.3,0.1

Type RM Length L Ch R = 1,42835,298,298,298
BEGIN DESCRIPTION:
Elm 02 18 42835.28
END DESCRIPTION:
XS GIS Cut Line= 3
      1631310.71      6824991.09      1631700.00      6825138.21
      1632091.00      6825275.90
#Sta/Elev= 30
  4584.6 1957.19  4641.9 1953.89  4696.1 1952.12  4727.1 1950.19  4732.5 1950.64
  4749.5 1948.14  4762.7 1947.09  4792.8 1945.41  4835.1 1944.10  4856.4 1941.79
  4872.7 1938.46  4897.5 1936.32  4909.9 1934.22  4920.6 1933.23  4972.0 1925.53
  4972.3 1925.03  4975.8 1925.03  4976.0 1925.53  4982.7 1926.88  5018.6 1926.66
  5037.9 1928.77  5137.1 1930.11  5230.0 1932.69  5260.9 1934.11  5286.6 1936.41
  5302.9 1939.65  5317.5 1940.88  5355.9 1945.79  5379.4 1947.29  5415.3 1948.09
#Mann=3,-1,0
  4584.6    0.05       0  4972.0    0.05       0  4976.0    0.05       0
Bank Sta=4972,4976
Exp/Cntr=0.3,0.1

Type RM Length L Ch R = 1,42537,158,158,158
BEGIN DESCRIPTION:
Elm 02 18 42536.63
END DESCRIPTION:
XS GIS Cut Line= 3
      1631181.77      6825418.16      1631655.72      6825422.06
      1632134.85      6825420.76
#Sta/Elev= 30
  4525.9 1960.62  4579.1 1959.48  4639.1 1957.05  4709.1 1951.43  4759.1 1949.33
  4809.1 1943.70  4839.1 1941.56  4849.1 1941.37  4869.1 1939.17  4879.1 1936.79
  4909.1 1932.01  4929.1 1929.99  4949.1 1928.90  4969.1 1926.41  4995.0 1924.12
  4995.3 1923.62  4998.8 1923.62  4999.0 1924.12  5039.1 1924.72  5089.1 1927.57
  5129.1 1929.00  5169.1 1929.60  5189.1 1930.53  5219.1 1930.85  5259.1 1932.71
  5269.1 1933.28  5289.1 1935.50  5349.1 1943.87  5369.1 1945.88  5479.0 1949.30
#Mann=3,-1,0
  4525.9    0.05       0  4995.0    0.05       0  4999.0    0.05       0
Bank Sta=4995,4999
Exp/Cntr=0.3,0.1

Type RM Length L Ch R = 1,42379,384,384,384
BEGIN DESCRIPTION:
Elm 02 18 42379
END DESCRIPTION:
XS GIS Cut Line= 3
      1631197.38      6825595.24      1631705.20      6825563.99
      1632155.75      6825545.76
#Sta/Elev= 30
  4492.7 1960.39  4560.4 1958.49  4630.6 1955.00  4660.6 1952.11  4680.7 1950.86
  4693.8 1950.69  4700.7 1949.84  4730.8 1948.13  4780.9 1942.75  4820.9 1940.28
  4850.4 1935.49  4855.4 1935.58  4871.0 1931.72  4921.1 1927.18  4941.2 1924.57
  4951.2 1923.94  4971.2 1924.24  4989.3 1923.80  4989.5 1923.30  4993.0 1923.30
  4993.3 1923.80  5021.1 1924.13  5081.3 1926.94  5171.4 1929.68  5231.5 1932.28
  5274.9 1935.60  5281.5 1937.12  5291.5 1938.43  5381.6 1946.93  5452.4 1948.63
#Mann=3,-1,0
  4492.7    0.05       0  4989.3    0.03       0  4993.3    0.05       0
Bank Sta=4989.3,4993.3
Exp/Cntr=0.3,0.1

Type RM Length L Ch R = 1,41995,529,529,529
BEGIN DESCRIPTION:
Elm 02 18 41994.66
END DESCRIPTION:
XS GIS Cut Line= 3
      1631355.85      6825996.06      1631806.12      6825917.94
      1632330.67      6825794.39
#Sta/Elev= 30
  4543.0 1957.62  4623.9 1954.52  4643.6 1953.05  4724.8 1948.60  4765.4 1944.14
  4826.3 1939.72  4846.6 1936.83  4852.5 1935.03  4866.9 1933.42  4887.2 1930.37
  4927.8 1926.17  4958.3 1923.66  4966.9 1921.67  4971.9 1921.29  4978.6 1919.57
  4986.7 1919.31  4987.0 1918.81  4990.5 1918.81  4990.7 1919.31  5070.8 1921.55
  5112.9 1923.98  5150.1 1924.79  5245.4 1929.15  5276.2 1929.96  5358.4 1936.06
  5399.5 1940.97  5414.5 1941.94  5440.6 1945.44  5462.0 1947.59  5538.9 1950.41
#Mann=3,-1,0
  4543.0    0.05       0  4986.7    0.03       0  4990.7    0.05       0
Bank Sta=4986.7,4990.7
Exp/Cntr=0.3,0.1

Type RM Length L Ch R = 1,41466,356,356,356
BEGIN DESCRIPTION:
Elm 02 18 41466.43
END DESCRIPTION:
XS GIS Cut Line= 3
      1631337.65      6826357.15      1632054.66      6826358.89
      1632551.46      6826334.66
#Sta/Elev= 30
  4282.9 1952.22  4340.3 1951.23  4380.3 1949.86  4450.3 1947.19  4500.3 1944.31
  4600.3 1941.01  4640.3 1937.00  4680.3 1934.60  4690.3 1933.25  4720.3 1931.41
  4740.3 1929.13  4780.3 1926.44  4850.3 1920.55  4880.3 1919.07  4978.3 1916.46
  4978.5 1915.96  4982.0 1915.96  4982.3 1916.46  5002.6 1916.87  5040.3 1919.79
  5080.3 1921.05  5100.4 1922.57  5110.4 1923.71  5118.1 1925.27  5170.5 1929.03
  5210.5 1932.73  5270.6 1941.89  5290.6 1944.22  5380.7 1947.87  5497.3 1950.78
#Mann=3,-1,0
  4282.9    0.05       0  4978.3    0.03       0  4982.3    0.05       0
Bank Sta=4978.3,4982.3
Exp/Cntr=0.3,0.1

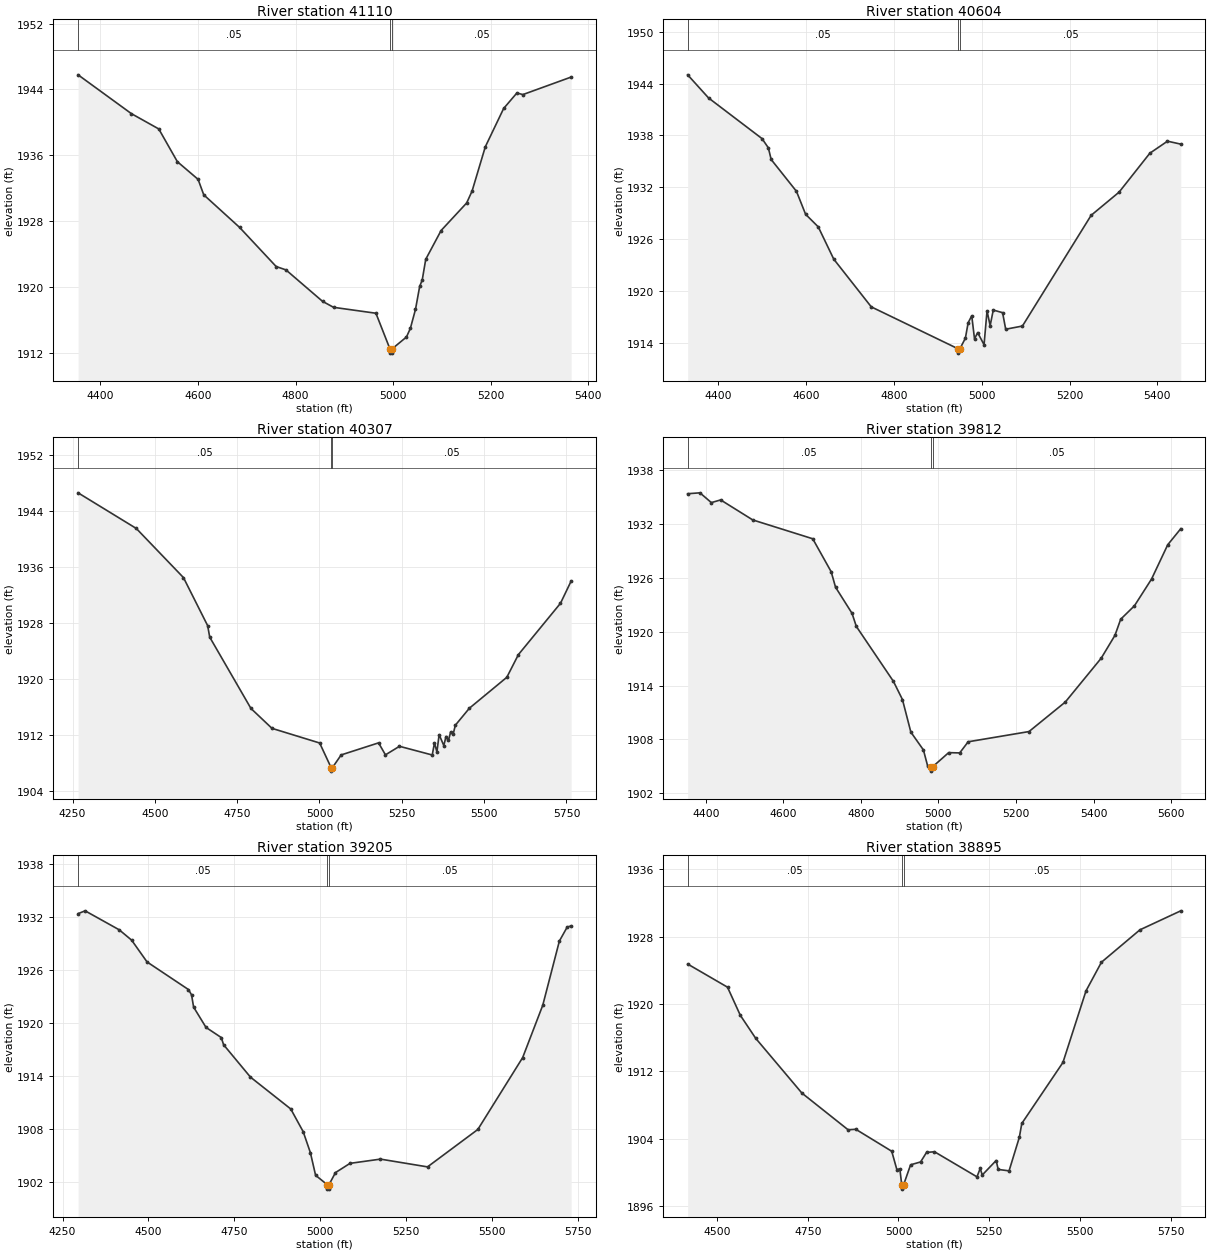
Type RM Length L Ch R = 1,41110,506,506,506
BEGIN DESCRIPTION:
Elm 02 18 41109.98
END DESCRIPTION:
XS GIS Cut Line= 3
      1631453.50      6826467.39      1632062.91      6826686.15
      1632409.27      6826795.52
#Sta/Elev= 30
  4354.2 1945.77  4463.5 1941.05  4519.6 1939.19  4557.7 1935.21  4600.2 1933.06
  4611.8 1931.18  4685.2 1927.22  4760.2 1922.46  4780.3 1922.05  4855.2 1918.23
  4877.8 1917.50  4964.7 1916.78  4993.5 1912.43  4993.7 1911.93  4997.2 1911.93
  4997.5 1912.43  5027.3 1913.89  5035.3 1914.94  5045.8 1917.25  5054.4 1920.05
  5059.6 1920.82  5066.8 1923.34  5098.3 1926.84  5150.7 1930.19  5161.8 1931.64
  5188.9 1937.02  5226.5 1941.68  5253.6 1943.56  5266.0 1943.37  5364.9 1945.50
#Mann=3,-1,0
  4354.2    0.05       0  4993.5    0.05       0  4997.5    0.05       0
Bank Sta=4993.5,4997.5
Exp/Cntr=0.3,0.1

Type RM Length L Ch R = 1,40604,297,297,297
BEGIN DESCRIPTION:
Elm 02 18 40604.42
END DESCRIPTION:
XS GIS Cut Line= 5
      1631393.65      6826571.58      1631758.22      6827027.29
      1631810.30      6827095.00      1631854.57      6827139.27
      1632245.23      6827126.25
#Sta/Elev= 30
  4330.7 1945.02  4378.3 1942.34  4500.0 1937.63  4514.4 1936.56  4520.8 1935.21
  4578.4 1931.52  4599.2 1928.86  4628.0 1927.40  4663.3 1923.66  4748.7 1918.13
  4946.4 1913.27  4946.6 1912.77  4950.4 1913.27  4962.9 1914.50  4969.2 1916.29
  4977.4 1917.10  4983.7 1914.43  4990.9 1915.15  5005.4 1913.74  5012.2 1917.67
  5019.3 1915.96  5026.4 1917.76  5047.6 1917.46  5054.7 1915.54  5092.8 1915.91
  5249.2 1928.74  5312.9 1931.43  5382.9 1935.94  5423.0 1937.33  5453.2 1936.99
#Mann=3,-1,0
  4330.7    0.05       0  4946.4    0.05       0  4950.4    0.05       0
Bank Sta=4946.4,4950.4
Exp/Cntr=0.3,0.1

Type RM Length L Ch R = 1,40307,495,495,495
BEGIN DESCRIPTION:
Elm 02 18 40306.95
END DESCRIPTION:
XS GIS Cut Line= 3
      1631034.40      6826957.13      1631659.44      6827341.27
      1632227.99      6827851.24
#Sta/Elev= 30
  4266.9 1946.56  4443.7 1941.48  4587.0 1934.47  4660.4 1927.62  4666.7 1925.98
  4791.8 1915.82  4855.7 1912.98  5000.5 1910.89  5035.3 1907.38  5035.6 1906.88
  5039.3 1907.38  5065.8 1909.19  5179.4 1910.91  5200.3 1909.20  5242.9 1910.42
  5342.4 1909.18  5349.1 1910.89  5356.6 1909.63  5363.3 1912.08  5377.5 1910.53
  5384.2 1911.81  5391.7 1911.26  5398.4 1912.48  5405.9 1912.16  5412.6 1913.43
  5455.2 1915.85  5568.9 1920.26  5604.0 1923.49  5731.8 1930.81  5764.3 1933.99
#Mann=3,-1,0
  4266.9    0.05       0  5035.3    0.03       0  5039.3    0.05       0
Bank Sta=5035.3,5039.3
Exp/Cntr=0.3,0.1

Type RM Length L Ch R = 1,39812,607,607,607
BEGIN DESCRIPTION:
Elm 02 18 39812.34
END DESCRIPTION:
XS GIS Cut Line= 3
      1630802.64      6827490.13      1631399.02      6827734.93
      1631905.66      6828103.87
#Sta/Elev= 30
  4353.5 1935.38  4385.2 1935.48  4414.6 1934.39  4438.6 1934.69  4521.3 1932.46
  4676.0 1930.36  4723.6 1926.68  4734.8 1924.96  4777.3 1922.05  4788.4 1920.59
  4884.0 1914.47  4907.3 1912.44  4929.0 1908.81  4961.4 1906.82  4972.2 1905.05
  4980.6 1904.96  4980.9 1904.46  4985.5 1904.96  5026.5 1906.52  5055.0 1906.49
  5076.7 1907.73  5233.6 1908.87  5327.2 1912.16  5419.8 1917.05  5455.3 1919.60
  5470.0 1921.39  5505.5 1922.89  5549.6 1925.87  5591.3 1929.69  5624.9 1931.48
#Mann=3,-1,0
  4353.5    0.05       0  4980.6    0.03       0  4985.5    0.05       0
Bank Sta=4980.6,4985.5
Exp/Cntr=0.3,0.1

Type RM Length L Ch R = 1,39205,310,310,310
BEGIN DESCRIPTION:
Elm 02 18 39204.84
END DESCRIPTION:
XS GIS Cut Line= 3
      1630367.76      6827698.47      1630956.31      6828089.10
      1631574.87      6828473.75
#Sta/Elev= 30
  4295.3 1932.37  4315.8 1932.69  4415.0 1930.54  4451.1 1929.37  4496.0 1926.90
  4616.5 1923.77  4625.5 1923.17  4631.5 1921.78  4667.6 1919.48  4712.1 1918.33
  4718.7 1917.52  4796.9 1913.85  4914.2 1910.24  4950.3 1907.67  4971.3 1905.29
  4986.4 1902.73  5020.4 1901.66  5020.8 1901.16  5025.0 1901.16  5025.4 1901.66
  5044.2 1903.03  5086.6 1904.08  5175.2 1904.56  5312.1 1903.68  5458.5 1907.92
  5588.9 1916.06  5647.4 1921.99  5695.8 1929.27  5718.5 1930.85  5730.1 1930.98
#Mann=3,-1,0
  4295.3    0.05       0  5020.4    0.05       0  5025.4    0.05       0
Bank Sta=5020.4,5025.4
Exp/Cntr=0.3,0.1

Type RM Length L Ch R = 1,38895,531,531,531
BEGIN DESCRIPTION:
Elm 02 18 38894.61
END DESCRIPTION:
XS GIS Cut Line= 4
      1630445.30      6827952.48      1630857.64      6828366.99
      1631105.04      6828499.37      1631440.71      6828861.03
#Sta/Elev= 30
  4419.2 1924.75  4529.0 1922.00  4564.3 1918.66  4606.8 1915.92  4734.0 1909.42
  4861.3 1905.06  4882.5 1905.12  4981.5 1902.51  4995.6 1900.34  5003.9 1900.41
  5009.1 1898.51  5009.5 1898.01  5014.1 1898.51  5033.5 1900.90  5061.1 1901.24
  5077.4 1902.37  5099.3 1902.45  5216.4 1899.47  5225.3 1900.47  5231.0 1899.69
  5269.2 1901.41  5274.9 1900.35  5304.8 1900.18  5333.1 1904.16  5339.9 1905.81
  5453.3 1913.06  5516.8 1921.56  5559.3 1924.96  5665.3 1928.81  5777.9 1931.07
#Mann=3,-1,0
  4419.2    0.05       0  5009.1    0.03       0  5014.1    0.05       0
Bank Sta=5009.1,5014.1
Exp/Cntr=0.3,0.1

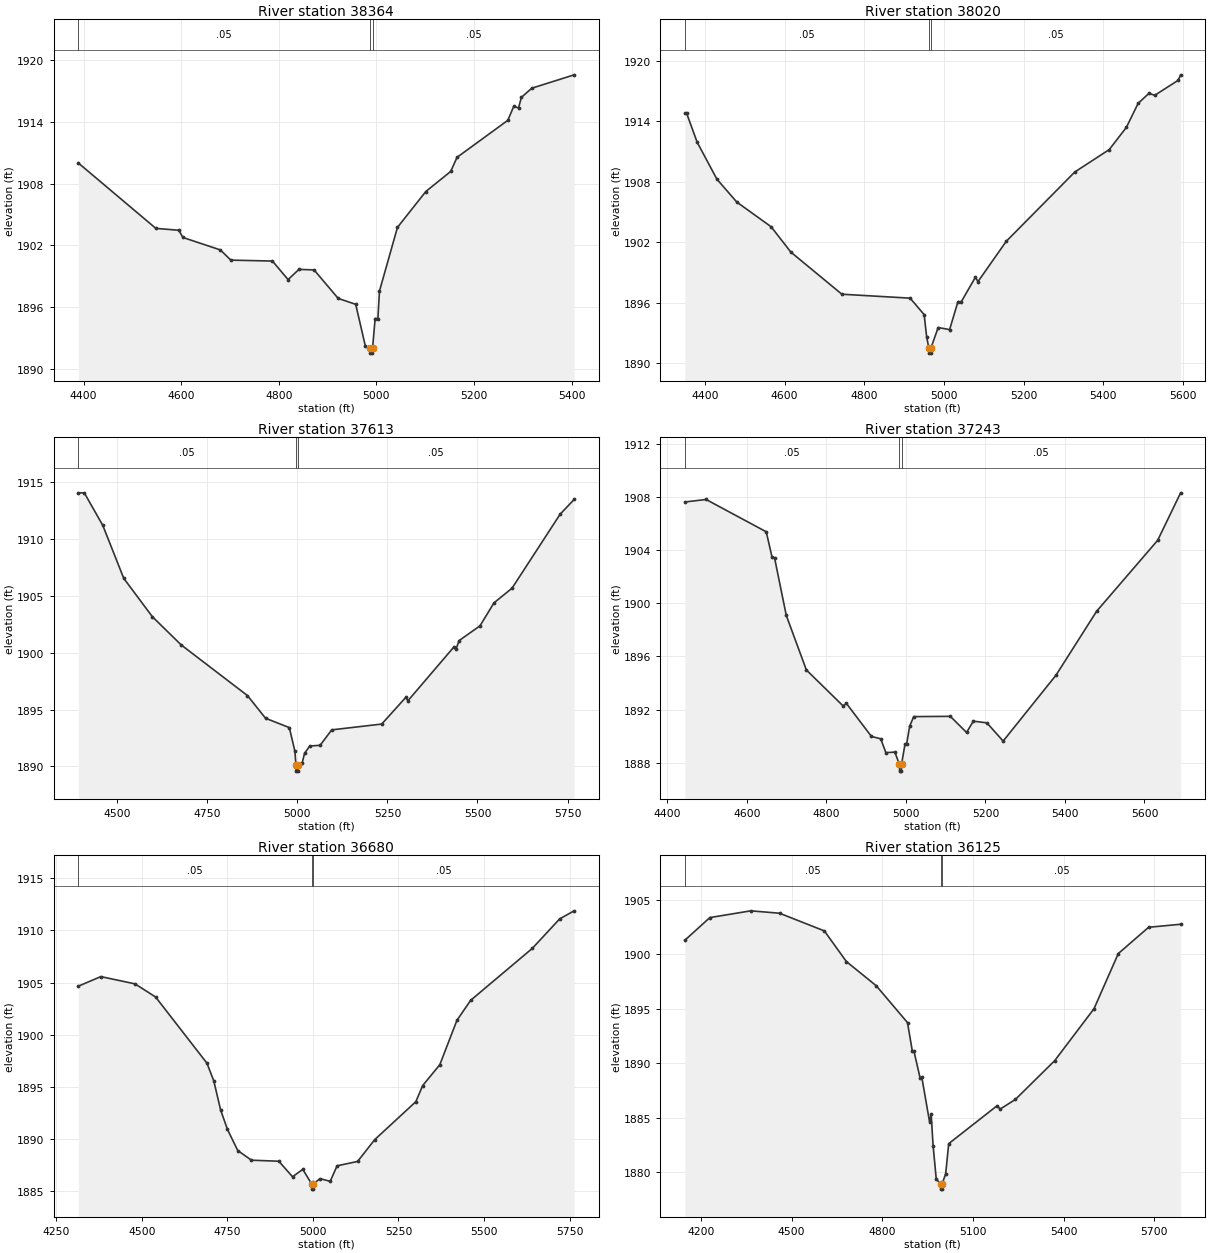
Type RM Length L Ch R = 1,38364,344,344,344
BEGIN DESCRIPTION:
Elm 02 18 38363.98
END DESCRIPTION:
XS GIS Cut Line= 3
      1630574.44      6828214.99      1630786.68      6828787.89
      1630996.84      6829134.27
#Sta/Elev= 30
  4389.2 1910.00  4548.1 1903.65  4595.0 1903.47  4603.5 1902.77  4680.3 1901.56
  4701.7 1900.57  4787.0 1900.48  4819.0 1898.68  4841.3 1899.67  4872.3 1899.62
  4921.8 1896.85  4957.6 1896.28  4977.3 1892.25  4987.1 1892.04  4987.5 1891.54
  4991.8 1891.54  4992.2 1892.04  4997.5 1894.90  5003.1 1894.90  5006.3 1897.56
  5043.2 1903.75  5101.3 1907.23  5152.3 1909.18  5165.3 1910.55  5269.3 1914.14
  5281.6 1915.51  5291.3 1915.34  5297.1 1916.37  5318.5 1917.26  5405.3 1918.56
#Mann=3,-1,0
  4389.2    0.05       0  4987.1    0.05       0  4992.2    0.05       0
Bank Sta=4987.1,4992.2
Exp/Cntr=0.3,0.1

Type RM Length L Ch R = 1,38020,407,407,407
BEGIN DESCRIPTION:
Elm 02 18 38019.89
END DESCRIPTION:
XS GIS Cut Line= 3
      1630092.89      6828435.90      1630500.87      6828945.88
      1630980.16      6829292.87
#Sta/Elev= 30
  4349.4 1914.79  4353.9 1914.79  4380.4 1911.91  4430.1 1908.24  4480.1 1905.97
  4566.1 1903.53  4615.8 1901.01  4743.8 1896.84  4915.1 1896.45  4950.3 1894.82
  4956.7 1892.59  4962.2 1891.50  4962.6 1891.00  4966.9 1891.00  4967.3 1891.50
  4985.5 1893.54  5014.2 1893.33  5035.1 1896.10  5043.6 1896.10  5079.2 1898.54
  5085.3 1898.08  5156.5 1902.09  5328.6 1908.96  5415.0 1911.18  5458.0 1913.38
  5487.5 1915.76  5514.5 1916.75  5529.2 1916.56  5587.8 1918.04  5594.2 1918.59
#Mann=3,-1,0
  4349.4    0.05       0  4962.2    0.05       0  4967.3    0.05       0
Bank Sta=4962.2,4967.3
Exp/Cntr=0.3,0.1

Type RM Length L Ch R = 1,37613,370,370,370
BEGIN DESCRIPTION:
Elm 02 18 37612.72
END DESCRIPTION:
XS GIS Cut Line= 4
      1629845.51      6828613.88      1630160.16      6829132.51
      1630220.92      6829208.46      1630819.64      6829513.22
#Sta/Elev= 30
  4392.5 1914.06  4409.0 1914.06  4460.3 1911.20  4518.5 1906.54  4598.0 1903.16
  4678.0 1900.68  4861.6 1896.23  4912.0 1894.23  4977.9 1893.41  4993.4 1891.33
  4996.4 1890.08  4996.8 1889.58  5001.2 1889.58  5001.6 1890.08  5013.7 1890.32
  5020.1 1891.14  5034.5 1891.79  5063.3 1891.85  5095.6 1893.21  5234.3 1893.72
  5301.1 1896.07  5306.7 1895.76  5434.5 1900.50  5440.1 1900.28  5448.8 1901.06
  5506.9 1902.36  5545.7 1904.38  5595.8 1905.67  5729.3 1912.18  5768.2 1913.48
#Mann=3,-1,0
  4392.5    0.05       0  4996.4    0.03       0  5001.6    0.05       0
Bank Sta=4996.4,5001.6
Exp/Cntr=0.3,0.1

Type RM Length L Ch R = 1,37243,563,563,563
BEGIN DESCRIPTION:
Elm 02 18 37243.17
END DESCRIPTION:
XS GIS Cut Line= 3
      1629512.68      6829104.69      1629967.52      6829427.59
      1630641.45      6829571.38
#Sta/Elev= 30
  4444.0 1907.61  4497.5 1907.80  4648.8 1905.37  4663.6 1903.44  4669.7 1903.41
  4699.2 1899.08  4749.7 1894.98  4841.9 1892.28  4850.5 1892.46  4913.3 1889.98
  4936.7 1889.80  4949.7 1888.76  4972.3 1888.80  4983.8 1887.87  4984.2 1887.37
  4988.6 1887.37  4989.0 1887.87  4997.8 1889.40  5001.8 1889.40  5009.5 1890.75
  5019.7 1891.47  5111.7 1891.49  5152.6 1890.28  5169.7 1891.13  5203.7 1891.00
  5244.6 1889.63  5377.6 1894.59  5479.8 1899.40  5633.2 1904.73  5690.9 1908.30
#Mann=3,-1,0
  4444.0    0.05       0  4983.8    0.03       0  4989.0    0.05       0
Bank Sta=4983.8,4989
Exp/Cntr=0.3,0.1

Type RM Length L Ch R = 1,36680,555,555,555
BEGIN DESCRIPTION:
Elm 02 18 36679.53
END DESCRIPTION:
XS GIS Cut Line= 3
      1629219.27      6829850.77      1629906.76      6829855.98
      1630667.21      6829882.02
#Sta/Elev= 30
  4314.9 1904.65  4380.6 1905.57  4480.6 1904.87  4540.6 1903.61  4690.6 1897.25
  4710.6 1895.55  4730.6 1892.75  4750.6 1890.88  4780.6 1888.86  4820.6 1887.93
  4900.6 1887.83  4940.6 1886.34  4970.6 1887.05  4996.4 1885.65  4996.8 1885.15
  5001.3 1885.15  5001.7 1885.65  5020.7 1886.16  5050.7 1885.90  5070.7 1887.39
  5130.7 1887.81  5180.8 1889.91  5300.8 1893.55  5320.8 1895.10  5370.9 1897.11
  5420.9 1901.37  5460.9 1903.29  5641.0 1908.28  5721.1 1911.12  5763.3 1911.89
#Mann=3,-1,0
  4314.9    0.05       0  4996.4    0.05       0  5001.7    0.05       0
Bank Sta=4996.4,5001.7
Exp/Cntr=0.3,0.1

Type RM Length L Ch R = 1,36125,852,852,852
BEGIN DESCRIPTION:
Elm 02 18 36125.01
END DESCRIPTION:
XS GIS Cut Line= 3
      1629048.78      6830116.90      1629851.78      6830394.69
      1630640.85      6830442.38
#Sta/Elev= 30
  4146.6 1901.27  4229.5 1903.35  4364.8 1903.97  4460.0 1903.75  4608.2 1902.13
  4681.1 1899.32  4779.9 1897.10  4883.3 1893.72  4899.3 1891.10  4904.6 1891.10
  4925.1 1888.63  4930.4 1888.75  4956.3 1884.62  4961.6 1885.32  4968.0 1882.43
  4978.5 1879.36  4992.7 1878.95  4993.1 1878.45  4997.6 1878.45  4998.0 1878.95
  5009.5 1879.84  5019.6 1882.62  5179.8 1886.10  5189.9 1885.79  5240.0 1886.67
  5370.2 1890.23  5500.4 1895.00  5580.6 1900.05  5680.8 1902.46  5786.8 1902.74
#Mann=3,-1,0
  4146.6    0.05       0  4992.7    0.05       0  4998.0    0.05       0
Bank Sta=4992.7,4998
Exp/Cntr=0.3,0.1

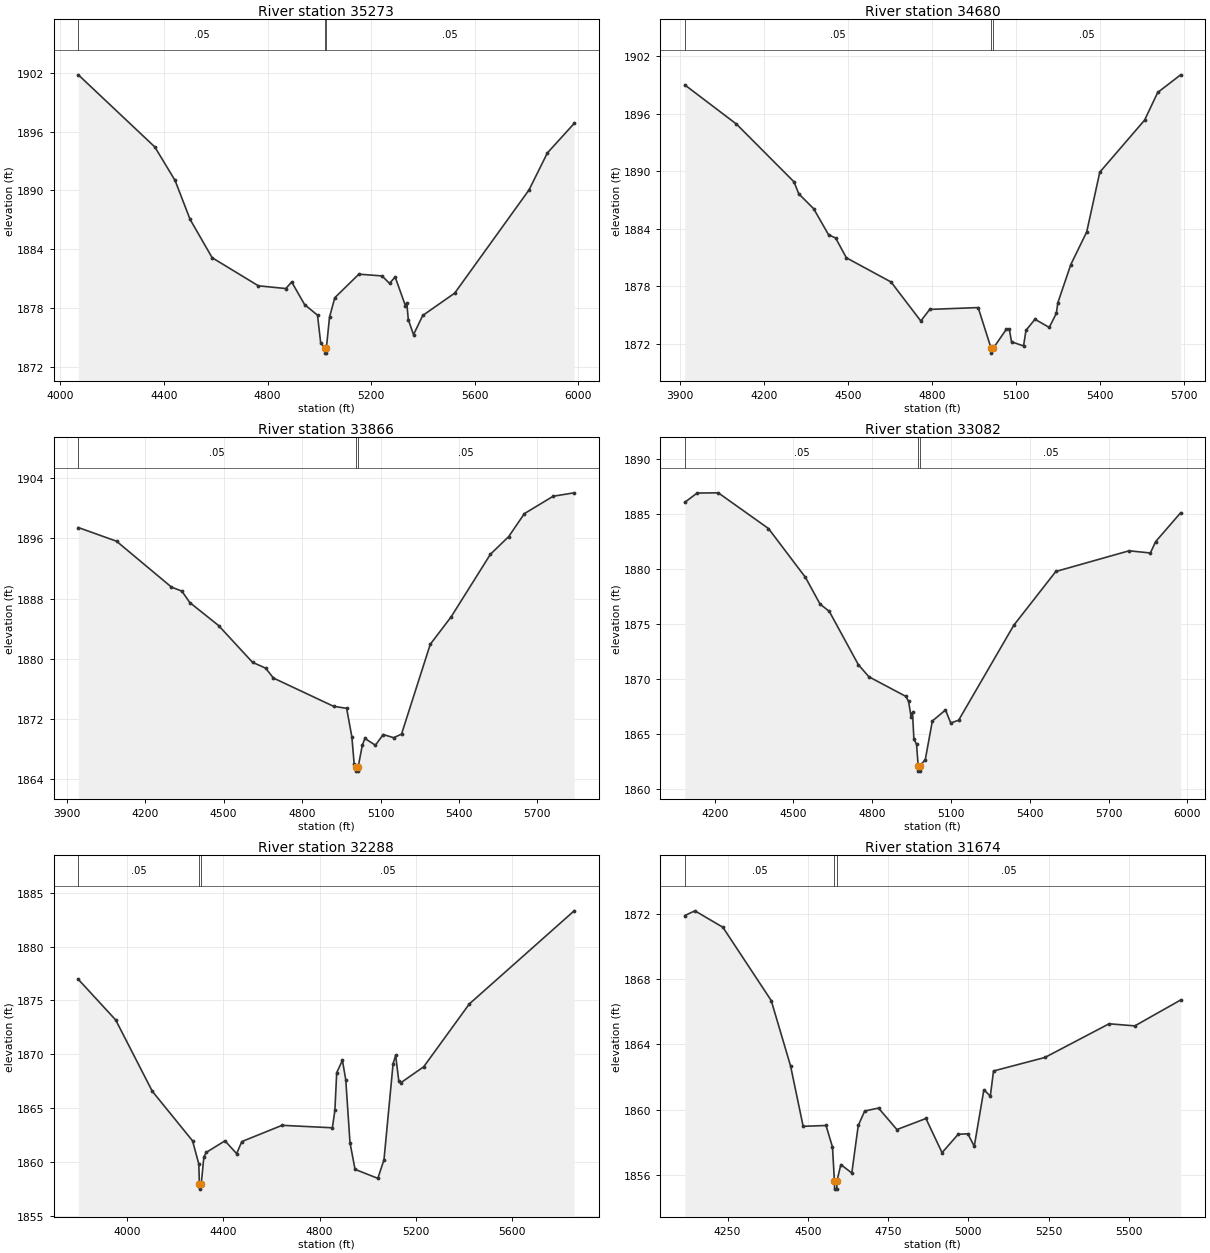
Type RM Length L Ch R = 1,35273,593,593,593
BEGIN DESCRIPTION:
Elm 02 18 35273.04
END DESCRIPTION:
XS GIS Cut Line= 3
      1629374.34      6830364.29      1629947.27      6831106.50
      1630103.51      6832069.99
#Sta/Elev= 30
  4069.7 1901.81  4364.9 1894.44  4443.0 1891.02  4501.0 1887.04  4586.2 1883.12
  4764.6 1880.25  4870.5 1879.97  4893.2 1880.64  4943.0 1878.33  4992.8 1877.25
  5005.1 1874.43  5021.5 1873.87  5022.0 1873.37  5026.5 1873.37  5026.9 1873.87
  5039.2 1877.04  5059.5 1879.03  5152.5 1881.44  5241.8 1881.26  5270.7 1880.50
  5292.5 1881.15  5332.3 1878.21  5337.4 1878.51  5343.2 1876.80  5363.4 1875.26
  5399.0 1877.22  5522.3 1879.50  5809.2 1890.05  5880.1 1893.83  5983.4 1896.84
#Mann=3,-1,0
  4069.7    0.05       0  5021.5    0.05       0  5026.9    0.05       0
Bank Sta=5021.5,5026.9
Exp/Cntr=0.3,0.1

Type RM Length L Ch R = 1,34680,814,814,814
BEGIN DESCRIPTION:
Elm 02 18 34680.34
END DESCRIPTION:
XS GIS Cut Line= 3
      1629139.97      6830425.04      1629504.56      6831449.38
      1629634.78      6832117.82
#Sta/Elev= 30
  3918.4 1899.02  4102.4 1894.94  4307.6 1888.92  4324.9 1887.66  4378.0 1886.11
  4431.0 1883.40  4456.4 1883.05  4494.7 1880.99  4653.9 1878.47  4760.1 1874.40
  4791.9 1875.61  4964.7 1875.80  5010.8 1871.55  5011.3 1871.05  5018.2 1871.55
  5065.4 1873.55  5075.6 1873.59  5083.6 1872.23  5126.5 1871.80  5135.2 1873.43
  5167.3 1874.58  5218.2 1873.73  5243.5 1875.21  5248.8 1876.30  5295.1 1880.29
  5351.8 1883.69  5398.4 1889.92  5558.3 1895.35  5604.9 1898.23  5686.7 1900.07
#Mann=3,-1,0
  3918.4    0.05       0  5010.8    0.05       0  5018.2    0.05       0
Bank Sta=5010.8,5018.2
Exp/Cntr=0.3,0.1

Type RM Length L Ch R = 1,33866,784,784,784
BEGIN DESCRIPTION:
Elm 02 18 33865.9
END DESCRIPTION:
XS GIS Cut Line= 3
      1628870.88      6830381.67      1628862.20      6831440.70
      1628870.88      6832278.39
#Sta/Elev= 30
  3944.0 1897.45  4090.3 1895.63  4300.3 1889.54  4340.3 1889.00  4370.3 1887.49
  4480.4 1884.44  4610.4 1879.55  4660.4 1878.78  4690.4 1877.46  4920.4 1873.71
  4970.4 1873.44  4990.4 1869.65  4999.2 1866.04  5006.6 1865.60  5007.1 1865.10
  5013.7 1865.10  5014.2 1865.60  5030.4 1868.55  5040.4 1869.44  5080.4 1868.54
  5110.4 1869.96  5150.4 1869.54  5180.4 1870.02  5290.4 1881.95  5370.4 1885.60
  5520.4 1893.90  5590.4 1896.25  5650.4 1899.30  5760.7 1901.61  5840.8 1902.06
#Mann=3,-1,0
  3944.0    0.05       0  5006.6    0.05       0  5014.2    0.05       0
Bank Sta=5006.6,5014.2
Exp/Cntr=0.3,0.1

Type RM Length L Ch R = 1,33082,794,794,794
BEGIN DESCRIPTION:
Elm 02 18 33081.63
END DESCRIPTION:
XS GIS Cut Line= 3
      1628228.59      6830581.45      1628124.43      6831491.13
      1628131.37      6832463.18
#Sta/Elev= 30
  4086.2 1886.06  4133.1 1886.90  4213.6 1886.92  4404.8 1883.68  4545.7 1879.24
  4601.2 1876.82  4636.3 1876.16  4747.0 1871.32  4787.3 1870.22  4928.2 1868.44
  4938.3 1867.98  4948.1 1866.53  4953.1 1867.00  4958.4 1864.56  4968.5 1864.10
  4974.7 1862.16  4975.2 1861.66  4981.9 1861.66  4982.4 1862.16  5001.8 1862.71
  5028.7 1866.21  5078.7 1867.21  5098.7 1866.03  5128.7 1866.28  5338.7 1874.90
  5498.7 1879.78  5777.9 1881.66  5858.7 1881.46  5878.7 1882.49  5973.9 1885.11
#Mann=3,-1,0
  4086.2    0.05       0  4974.7    0.05       0  4982.4    0.05       0
Bank Sta=4974.7,4982.4
Exp/Cntr=0.3,0.1

Type RM Length L Ch R = 1,32288,614,614,614
BEGIN DESCRIPTION:
Elm 02 18 32287.94
END DESCRIPTION:
XS GIS Cut Line= 3
      1627048.03      6830539.72      1627409.15      6831692.52
      1627693.86      6832498.04
#Sta/Elev= 30
  3796.7 1876.95  3952.1 1873.18  4104.2 1866.56  4271.7 1861.95  4297.9 1859.79
  4300.2 1857.96  4300.7 1857.46  4308.0 1857.96  4318.9 1860.45  4329.3 1860.88
  4406.7 1861.95  4455.1 1860.76  4476.8 1861.88  4644.3 1863.39  4853.3 1863.16
  4863.8 1864.77  4871.4 1868.28  4895.2 1869.43  4909.1 1867.62  4926.7 1861.78
  4947.6 1859.30  5042.5 1858.46  5068.1 1860.19  5106.0 1869.13  5116.6 1869.88
  5129.9 1867.48  5137.8 1867.34  5233.3 1868.83  5423.1 1874.67  5859.1 1883.32
#Mann=3,-1,0
  3796.7    0.05       0  4300.2    0.05       0  4308.0    0.05       0
Bank Sta=4300.2,4308
Exp/Cntr=0.3,0.1

Type RM Length L Ch R = 1,31674,685,685,685
BEGIN DESCRIPTION:
Elm 02 18 31673.7
END DESCRIPTION:
XS GIS Cut Line= 3
      1626747.40      6830709.89      1626825.53      6831599.64
      1626829.87      6832250.66
#Sta/Elev= 30
  4117.0 1871.92  4148.5 1872.21  4235.6 1871.20  4386.1 1866.70  4446.4 1862.68
  4485.6 1858.97  4556.8 1859.02  4576.9 1857.70  4583.0 1855.61  4583.5 1855.11
  4590.4 1855.11  4590.9 1855.61  4603.0 1856.62  4637.1 1856.10  4657.2 1859.02
  4677.3 1859.91  4720.4 1860.09  4777.6 1858.77  4868.0 1859.45  4918.2 1857.35
  4968.4 1858.48  4998.5 1858.51  5018.5 1857.74  5048.5 1861.22  5068.5 1860.82
  5078.5 1862.37  5238.5 1863.20  5438.5 1865.27  5518.5 1865.14  5661.2 1866.73
#Mann=3,-1,0
  4117.0    0.05       0  4583.0    0.05       0  4590.9    0.05       0
Bank Sta=4583,4590.9
Exp/Cntr=0.3,0.1

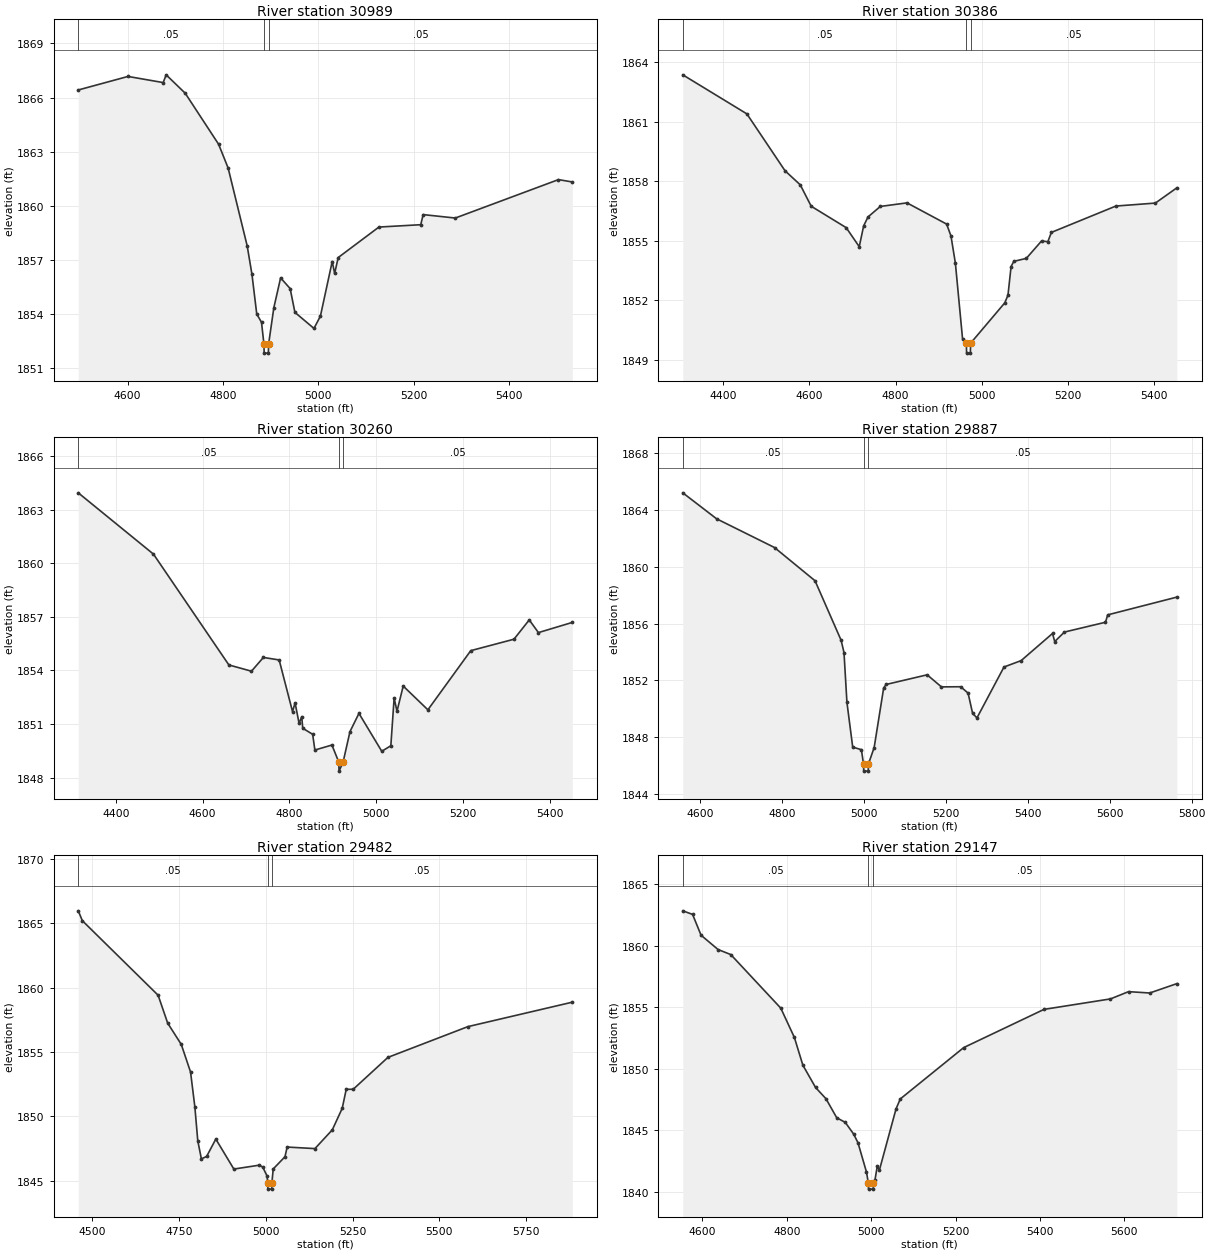
Type RM Length L Ch R = 1,30989,603,603,603
BEGIN DESCRIPTION:
Elm 02 18 30988.77
END DESCRIPTION:
XS GIS Cut Line= 3
      1626352.44      6830783.71      1626374.14      6831291.48
      1626486.98      6831807.97
#Sta/Elev= 30
  4496.4 1866.42  4600.8 1867.17  4674.7 1866.83  4680.9 1867.26  4720.9 1866.24
  4791.0 1863.41  4811.0 1862.09  4851.0 1857.77  4861.0 1856.19  4871.0 1854.00
  4881.0 1853.54  4886.1 1852.33  4886.6 1851.83  4895.4 1851.83  4895.9 1852.33
  4906.9 1854.35  4921.1 1856.00  4941.1 1855.41  4951.1 1854.09  4991.1 1853.20
  5004.6 1853.88  5029.4 1856.91  5034.5 1856.25  5042.0 1857.13  5127.4 1858.82
  5215.2 1858.95  5220.3 1859.51  5287.7 1859.32  5504.2 1861.45  5533.3 1861.32
#Mann=3,-1,0
  4496.4    0.05       0  4886.1    0.05       0  4895.9    0.05       0
Bank Sta=4886.1,4895.9
Exp/Cntr=0.3,0.1

Type RM Length L Ch R = 1,30386,126,126,126
BEGIN DESCRIPTION:
Elm 02 18 30385.52
END DESCRIPTION:
XS GIS Cut Line= 3
      1625933.22      6830553.95      1625822.11      6831244.89
      1626092.96      6831599.08
#Sta/Elev= 30
  4306.5 1863.37  4455.1 1861.40  4543.6 1858.53  4578.9 1857.82  4604.3 1856.74
  4685.4 1855.66  4715.7 1854.70  4725.9 1855.75  4736.0 1856.20  4764.5 1856.73
  4826.4 1856.91  4918.3 1855.84  4928.4 1855.24  4938.6 1853.87  4955.2 1850.06
  4964.1 1849.83  4964.6 1849.33  4973.4 1849.33  4973.9 1849.83  5053.3 1851.87
  5060.6 1852.26  5067.8 1853.70  5074.1 1853.96  5103.1 1854.11  5138.5 1854.99
  5153.0 1854.95  5161.2 1855.42  5310.8 1856.75  5402.4 1856.90  5452.2 1857.67
#Mann=3,-1,0
  4306.5    0.05       0  4964.1    0.05       0  4973.9    0.05       0
Bank Sta=4964.1,4973.9
Exp/Cntr=0.3,0.1

Type RM Length L Ch R = 1,30260,373,373,373
BEGIN DESCRIPTION:
Elm 02 18 30096.19
END DESCRIPTION:
XS GIS Cut Line= 4
      1625211.79      6830812.36      1625653.71      6831084.91
      1625698.84      6831245.89      1625996.16      6831586.87
#Sta/Elev= 30
  4313.6 1863.94  4487.0 1860.51  4660.8 1854.31  4712.9 1853.96  4740.3 1854.73
  4776.7 1854.59  4807.5 1851.70  4813.4 1852.19  4822.6 1851.04  4828.8 1851.42
  4831.0 1850.77  4853.9 1850.43  4859.0 1849.55  4898.3 1849.83  4914.2 1848.87
  4914.7 1848.37  4924.0 1848.87  4939.9 1850.58  4960.6 1851.60  5013.2 1849.48
  5034.1 1849.79  5041.7 1852.46  5048.3 1851.72  5062.6 1853.13  5119.5 1851.80
  5218.3 1855.11  5317.9 1855.75  5353.1 1856.83  5374.3 1856.12  5452.4 1856.69
#Mann=3,-1,0
  4313.6    0.05       0  4914.2    0.03       0  4924.0    0.05       0
Bank Sta=4914.2,4924
Exp/Cntr=0.3,0.1

Type RM Length L Ch R = 1,29887,405,405,405
BEGIN DESCRIPTION:
Elm 02 18 29887.18
END DESCRIPTION:
XS GIS Cut Line= 3
      1625054.70      6831061.45      1625375.87      6831373.94
      1626074.69      6831669.10
#Sta/Elev= 30
  4557.2 1865.20  4639.9 1863.37  4781.2 1861.35  4880.2 1859.01  4943.9 1854.82
  4950.9 1853.96  4958.1 1850.45  4972.2 1847.30  4993.4 1847.12  4998.6 1846.11
  4999.1 1845.61  5010.1 1845.61  5010.6 1846.11  5024.6 1847.27  5047.8 1851.46
  5053.7 1851.71  5154.0 1852.39  5188.9 1851.54  5236.0 1851.55  5254.0 1851.10
  5265.1 1849.67  5275.7 1849.36  5341.7 1852.94  5383.6 1853.39  5460.2 1855.30
  5465.6 1854.73  5489.3 1855.40  5589.6 1856.09  5595.0 1856.61  5763.9 1857.86
#Mann=3,-1,0
  4557.2    0.05       0  4998.6    0.03       0  5010.6    0.05       0
Bank Sta=4998.6,5010.6
Exp/Cntr=0.3,0.1

Type RM Length L Ch R = 1,29482,335,335,335
BEGIN DESCRIPTION:
Elm 02 18 29481.83
END DESCRIPTION:
XS GIS Cut Line= 3
      1624733.51      6831582.28      1625254.35      6831729.85
      1626135.47      6831781.93
#Sta/Elev= 30
  4459.1 1865.97  4471.0 1865.20  4689.3 1859.41  4716.9 1857.24  4756.0 1855.59
  4782.8 1853.44  4795.2 1850.73  4803.6 1848.10  4814.0 1846.69  4829.1 1846.88
  4855.6 1848.23  4907.6 1845.90  4980.4 1846.20  4990.7 1846.06  5003.3 1845.36
  5005.1 1844.84  5005.6 1844.34  5016.7 1844.34  5017.2 1844.84  5021.1 1845.91
  5055.0 1846.86  5061.2 1847.61  5141.3 1847.49  5191.4 1848.95  5219.9 1850.62
  5231.5 1852.10  5251.5 1852.10  5351.7 1854.58  5582.1 1856.97  5883.1 1858.87
#Mann=3,-1,0
  4459.1    0.05       0  5005.1    0.05       0  5017.2    0.05       0
Bank Sta=5005.1,5017.2
Exp/Cntr=0.3,0.1

Type RM Length L Ch R = 1,29147,422,422,422
BEGIN DESCRIPTION:
Elm 02 18 29147.2
END DESCRIPTION:
XS GIS Cut Line= 3
      1624711.86      6831990.27      1625158.86      6832033.67
      1625879.30      6831994.61
#Sta/Elev= 30
  4553.8 1862.83  4577.0 1862.54  4597.1 1860.85  4637.3 1859.69  4667.5 1859.28
  4786.0 1854.93  4818.2 1852.55  4838.3 1850.30  4868.4 1848.49  4893.0 1847.58
  4918.6 1846.03  4938.7 1845.66  4958.8 1844.70  4968.9 1844.00  4989.0 1841.63
  4993.4 1840.74  4993.9 1840.24  5005.0 1840.24  5005.5 1840.74  5009.1 1840.98
  5014.6 1842.11  5019.6 1841.78  5059.1 1846.76  5069.1 1847.56  5219.4 1851.73
  5409.6 1854.83  5567.1 1855.68  5609.9 1856.27  5660.0 1856.16  5724.4 1856.92
#Mann=3,-1,0
  4553.8    0.05       0  4993.4    0.05       0  5005.5    0.05       0
Bank Sta=4993.4,5005.5
Exp/Cntr=0.3,0.1