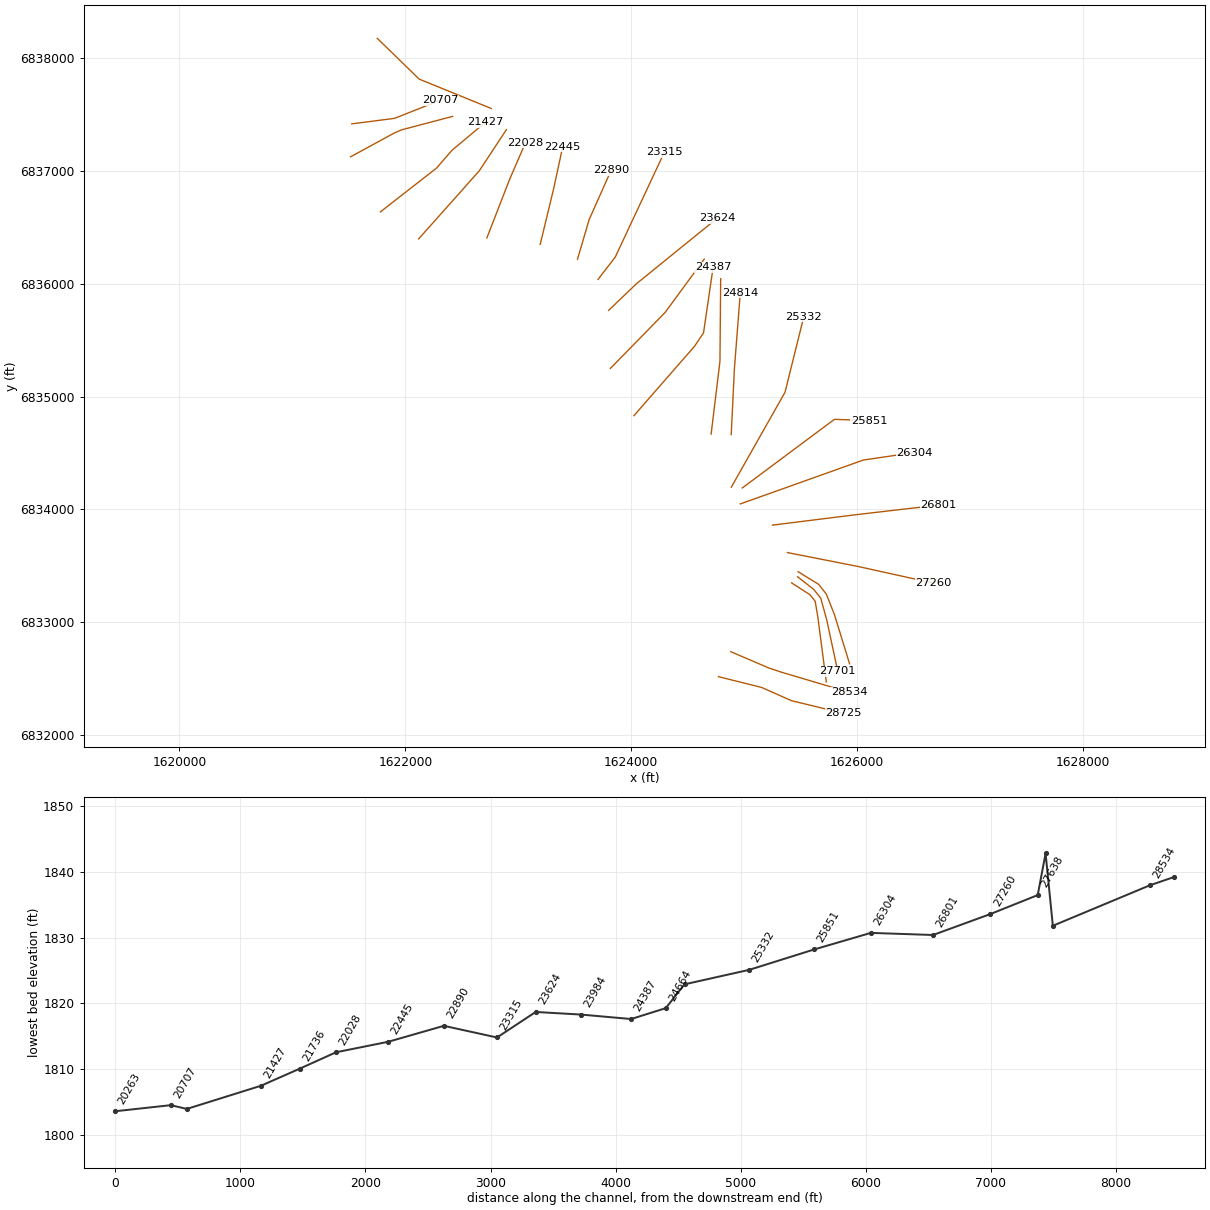
HEC-RAS study Elm 02 18.prj: Elm 02 18 Base Level Engineering

--- Elm 02 18.g01 (geometry) --- (continued)

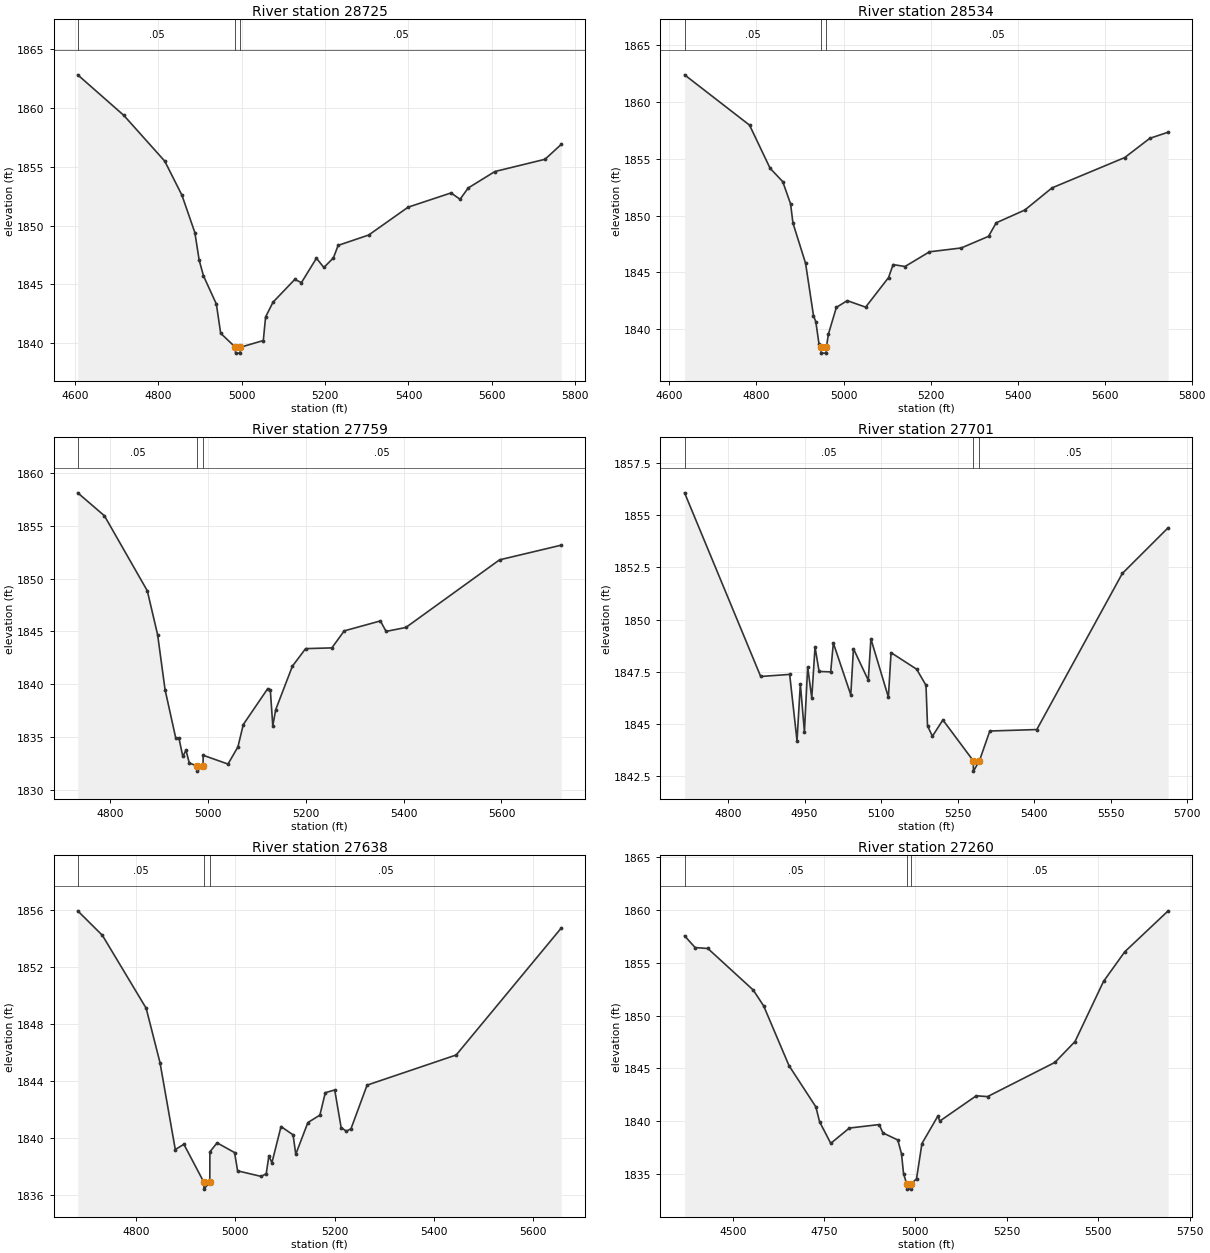
Type RM Length L Ch R = 1,28725,191,191,191
BEGIN DESCRIPTION:
Elm 02 18 28725.06
END DESCRIPTION:
XS GIS Cut Line= 4
      1624772.54      6832519.79      1625154.52      6832424.29
      1625419.28      6832307.10      1625881.85      6832194.70
#Sta/Elev= 30
  4607.1 1862.81  4717.7 1859.36  4815.8 1855.47  4857.0 1852.57  4887.9 1849.40
  4898.3 1847.05  4908.6 1845.72  4939.5 1843.32  4949.8 1840.84  4985.0 1839.65
  4985.5 1839.15  4996.6 1839.15  4997.1 1839.65  5052.0 1840.22  5057.5 1842.23
  5075.3 1843.48  5127.3 1845.41  5143.5 1845.15  5179.4 1847.22  5197.2 1846.43
  5220.1 1847.25  5231.4 1848.31  5304.6 1849.19  5399.2 1851.56  5502.1 1852.77
  5523.7 1852.23  5543.2 1853.19  5607.2 1854.59  5727.3 1855.63  5766.4 1856.90
#Mann=3,-1,0
  4607.1    0.05       0  4985.0    0.05       0  4997.1    0.05       0
Bank Sta=4985,4997.1
Exp/Cntr=0.3,0.1

Type RM Length L Ch R = 1,28534,775,775,775
BEGIN DESCRIPTION:
Elm 02 18 28534.22
END DESCRIPTION:
XS GIS Cut Line= 4
      1624881.13      6832741.11      1625215.28      6832597.90
      1625332.47      6832558.84      1625930.75      6832381.09
#Sta/Elev= 30
  4634.8 1862.36  4784.1 1857.94  4831.3 1854.15  4860.3 1852.98  4878.4 1851.02
  4883.8 1849.34  4912.8 1845.81  4931.0 1841.21  4936.4 1840.66  4943.6 1838.73
  4948.4 1838.41  4948.9 1837.91  4960.1 1837.91  4960.6 1838.41  4965.4 1839.60
  4983.6 1841.93  5008.6 1842.52  5050.8 1841.95  5103.5 1844.55  5114.0 1845.69
  5141.3 1845.52  5197.5 1846.81  5270.6 1847.15  5333.2 1848.17  5350.9 1849.36
  5416.6 1850.48  5479.2 1852.43  5646.1 1855.09  5703.8 1856.78  5746.0 1857.32
#Mann=3,-1,0
  4634.8    0.05       0  4948.4    0.05       0  4960.6    0.05       0
Bank Sta=4948.4,4960.6
Exp/Cntr=0.3,0.1

Type RM Length L Ch R = 1,27759,58,58,58
BEGIN DESCRIPTION:
Elm 02 18 27758.79
END DESCRIPTION:
XS GIS Cut Line= 5
      1625420.23      6833350.04      1625581.70      6833245.86
      1625628.57      6833188.57      1625652.01      6833050.55
      1625727.49      6832472.74
#Sta/Elev= 30
  4733.4 1858.11  4788.0 1855.94  4875.7 1848.84  4896.8 1844.68  4912.0 1839.49
  4934.0 1834.88  4940.4 1834.89  4948.3 1833.17  4954.8 1833.76  4961.6 1832.54
  4977.4 1832.28  4977.9 1831.78  4989.6 1832.28  4990.0 1833.28  5040.7 1832.45
  5061.0 1834.07  5072.0 1836.19  5121.9 1839.58  5127.3 1839.42  5132.3 1836.07
  5138.3 1837.60  5172.4 1841.71  5199.4 1843.37  5253.1 1843.44  5278.4 1845.05
  5352.3 1845.99  5364.0 1845.00  5404.4 1845.37  5596.0 1851.77  5722.3 1853.16
#Mann=3,-1,0
  4733.4    0.05       0  4977.4    0.03       0  4989.6    0.05       0
Bank Sta=4977.4,4989.6
Exp/Cntr=0.3,0.1

Type RM Length L Ch R = 1,27701,63,63,63
BEGIN DESCRIPTION:
Elm 02 18 27701.29
END DESCRIPTION:
XS GIS Cut Line= 5
      1625472.30      6833404.74      1625615.55      6833292.74
      1625678.05      6833214.61      1625730.13      6833027.11
      1625829.09      6832566.20
#Sta/Elev= 30
  4714.9 1856.07  4864.1 1847.28  4920.9 1847.38  4935.3 1844.20  4941.8 1846.93
  4949.8 1844.63  4956.2 1847.74  4964.2 1846.25  4970.6 1848.69  4978.6 1847.52
  5001.3 1847.50  5006.5 1848.88  5040.7 1846.40  5045.9 1848.61  5075.0 1847.10
  5080.1 1849.08  5114.4 1846.29  5119.6 1848.42  5169.7 1847.63  5188.1 1846.86
  5191.1 1844.92  5200.7 1844.42  5221.2 1845.20  5280.7 1843.25  5281.2 1842.75
  5292.9 1843.25  5313.2 1844.67  5405.3 1844.74  5572.9 1852.21  5662.8 1854.40
#Mann=3,-1,0
  4714.9    0.05       0  5280.7    0.03       0  5292.9    0.05       0
Bank Sta=5280.7,5292.9
Exp/Cntr=0.3,0.1

Type RM Length L Ch R = 1,27638,378,378,378
BEGIN DESCRIPTION:
Elm 02 18 27638.27
END DESCRIPTION:
XS GIS Cut Line= 5
      1625477.52      6833448.99      1625659.82      6833337.01
      1625727.53      6833251.07      1625800.45      6833066.17
      1625933.25      6832633.93
#Sta/Elev= 30
  4682.3 1855.91  4732.1 1854.19  4820.2 1849.09  4848.1 1845.28  4878.9 1839.20
  4896.2 1839.57  4936.2 1836.93  4936.7 1836.43  4948.4 1836.93  4948.6 1839.04
  4963.1 1839.67  4998.3 1838.99  5004.4 1837.71  5052.0 1837.32  5062.1 1837.51
  5067.5 1838.77  5073.5 1838.27  5091.9 1840.81  5116.2 1840.23  5121.6 1838.87
  5146.0 1841.09  5170.2 1841.61  5181.1 1843.18  5200.1 1843.37  5213.0 1840.74
  5223.4 1840.49  5232.8 1840.65  5265.3 1843.71  5444.8 1845.82  5656.6 1854.71
#Mann=3,-1,0
  4682.3    0.05       0  4936.2    0.05       0  4948.4    0.05       0
Bank Sta=4936.2,4948.4
Exp/Cntr=0.3,0.1

Type RM Length L Ch R = 1,27260,459,459,459
BEGIN DESCRIPTION:
Elm 02 18 27259.64
END DESCRIPTION:
XS GIS Cut Line= 3
      1625382.53      6833618.70      1626000.62      6833497.16
      1626677.72      6833347.85
#Sta/Elev= 30
  4368.3 1857.57  4397.1 1856.46  4432.0 1856.37  4556.3 1852.43  4584.8 1850.92
  4654.0 1845.27  4727.5 1841.36  4737.7 1839.95  4768.3 1837.90  4819.2 1839.35
  4900.8 1839.68  4911.0 1838.89  4951.7 1838.22  4961.9 1836.91  4967.5 1835.03
  4976.1 1834.06  4976.6 1833.56  4988.0 1833.56  4988.5 1834.06  5003.0 1834.54
  5017.8 1837.88  5061.5 1840.49  5066.6 1840.01  5166.6 1842.41  5197.3 1842.33
  5381.6 1845.57  5436.7 1847.55  5514.7 1853.25  5572.9 1856.06  5691.6 1859.94
#Mann=3,-1,0
  4368.3    0.05       0  4976.1    0.05       0  4988.5    0.05       0
Bank Sta=4976.1,4988.5
Exp/Cntr=0.3,0.1

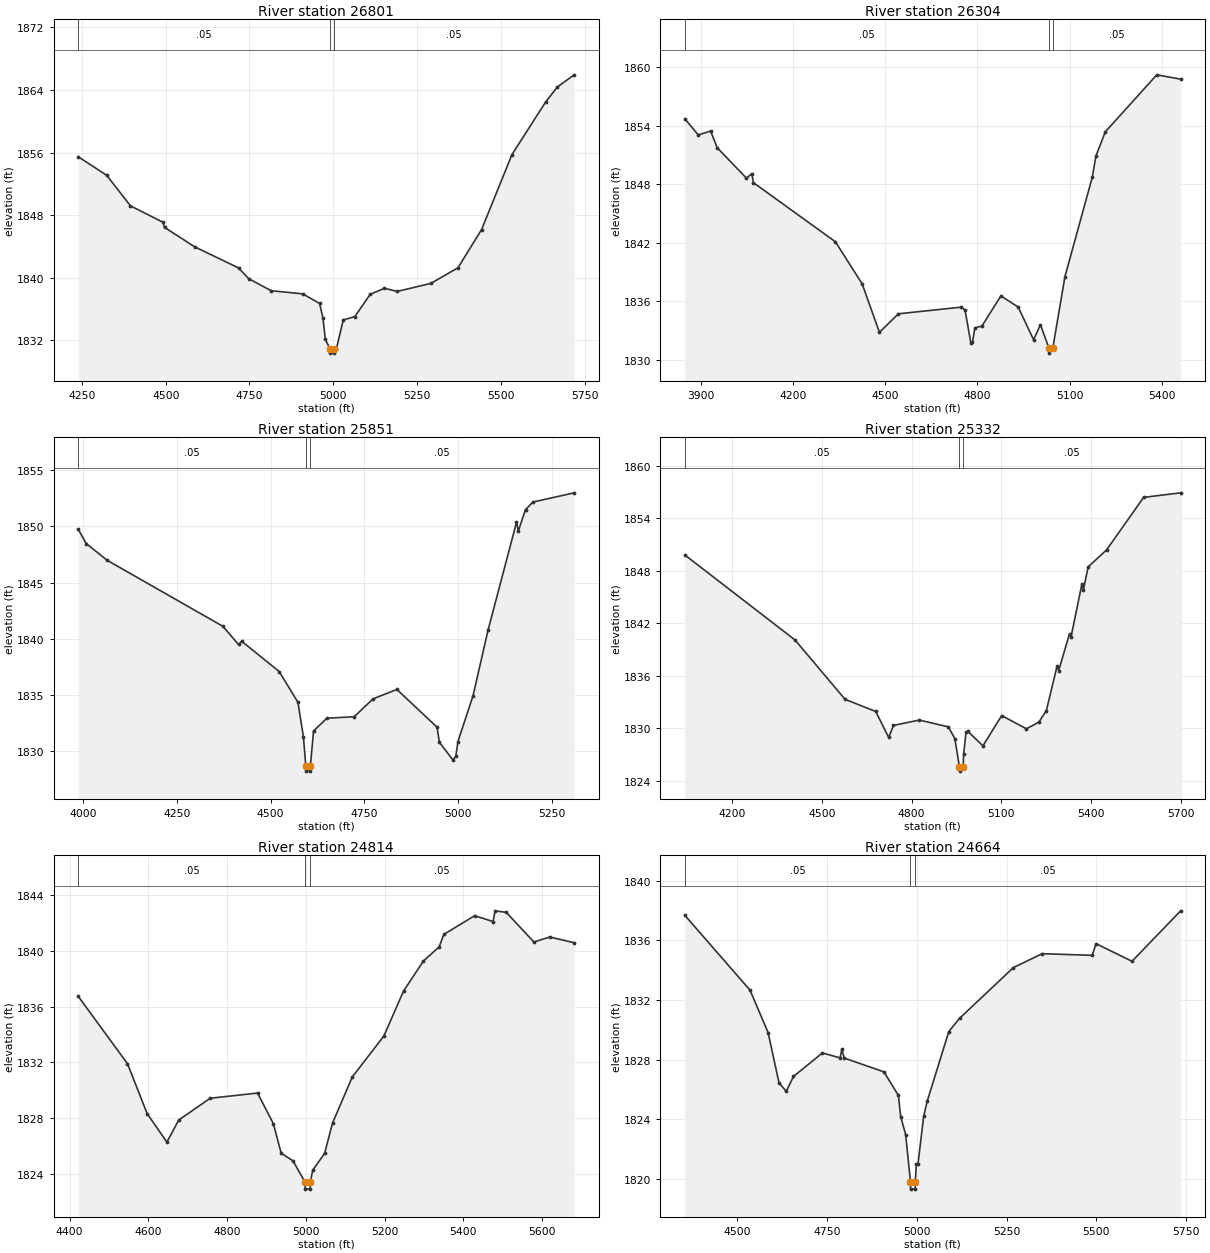
Type RM Length L Ch R = 1,26801,497,497,497
BEGIN DESCRIPTION:
Elm 02 18 26800.57
END DESCRIPTION:
XS GIS Cut Line= 3
      1625250.64      6833861.75      1626004.09      6833955.50
      1626719.39      6834038.83
#Sta/Elev= 30
  4239.3 1855.45  4324.3 1853.08  4394.8 1849.19  4491.5 1847.10  4496.5 1846.44
  4586.3 1843.96  4717.3 1841.26  4747.5 1839.89  4814.7 1838.35  4908.8 1837.95
  4959.2 1836.72  4969.2 1834.83  4976.3 1832.16  4990.3 1830.88  4990.8 1830.38
  5002.2 1830.38  5002.7 1830.88  5009.5 1830.97  5029.7 1834.62  5064.2 1835.04
  5110.2 1837.89  5152.7 1838.66  5190.8 1838.26  5291.4 1839.29  5372.0 1841.28
  5442.5 1846.16  5533.1 1855.73  5633.7 1862.46  5668.6 1864.37  5718.7 1865.92
#Mann=3,-1,0
  4239.3    0.05       0  4990.3    0.03       0  5002.7    0.05       0
Bank Sta=4990.3,5002.7
Exp/Cntr=0.3,0.1

Type RM Length L Ch R = 1,26304,453,453,453
BEGIN DESCRIPTION:
Elm 02 18 26304.08
END DESCRIPTION:
XS GIS Cut Line= 3
      1624965.87      6834049.24      1626056.18      6834438.14
      1626507.59      6834504.11
#Sta/Elev= 30
  3847.4 1854.71  3891.3 1853.05  3931.4 1853.45  3952.9 1851.74  4048.2 1848.62
  4065.5 1849.09  4070.9 1848.16  4337.5 1842.11  4424.6 1837.80  4480.9 1832.83
  4542.6 1834.73  4747.6 1835.41  4759.6 1835.10  4778.4 1831.75  4783.7 1831.79
  4791.4 1833.28  4814.5 1833.48  4876.3 1836.56  4932.5 1835.42  4982.5 1832.08
  5005.0 1833.61  5032.7 1831.20  5033.2 1830.70  5045.1 1831.20  5084.7 1838.54
  5173.7 1848.72  5185.7 1850.91  5216.0 1853.37  5383.6 1859.21  5461.2 1858.77
#Mann=3,-1,0
  3847.4    0.05       0  5032.7    0.05       0  5045.1    0.05       0
Bank Sta=5032.7,5045.1
Exp/Cntr=0.3,0.1

Type RM Length L Ch R = 1,25851,519,519,519
BEGIN DESCRIPTION:
Elm 02 18 25850.63
END DESCRIPTION:
XS GIS Cut Line= 3
      1624983.23      6834190.55      1625799.23      6834798.21
      1626104.75      6834787.79
#Sta/Elev= 30
  3986.8 1849.74  4007.7 1848.48  4064.0 1846.98  4372.6 1841.10  4414.3 1839.48
  4422.7 1839.77  4522.8 1837.07  4572.8 1834.33  4587.5 1831.23  4593.7 1828.69
  4594.2 1828.19  4605.6 1828.19  4606.1 1828.69  4614.5 1831.77  4650.0 1832.91
  4723.0 1833.04  4773.0 1834.63  4836.8 1835.47  4944.0 1832.11  4950.3 1830.76
  4986.5 1829.18  4994.1 1829.51  4999.8 1830.83  5040.0 1834.90  5080.0 1840.74
  5156.0 1850.36  5161.0 1849.60  5180.1 1851.51  5200.1 1852.18  5309.9 1853.00
#Mann=3,-1,0
  3986.8    0.05       0  4593.7    0.05       0  4606.1    0.05       0
Bank Sta=4593.7,4606.1
Exp/Cntr=0.3,0.1

Type RM Length L Ch R = 1,25332,518,518,518
BEGIN DESCRIPTION:
Elm 02 18 25332.37
END DESCRIPTION:
XS GIS Cut Line= 3
      1624886.05      6834197.53      1625361.73      6835037.79
      1625528.40      6835707.91
#Sta/Elev= 30
  4042.6 1849.82  4410.6 1840.10  4577.9 1833.31  4680.4 1831.92  4723.7 1828.95
  4739.6 1830.33  4826.1 1830.94  4922.8 1830.16  4944.5 1828.83  4959.9 1825.60
  4960.4 1825.10  4972.4 1825.60  4973.9 1827.05  4982.0 1829.54  4987.8 1829.66
  5038.3 1827.99  5101.1 1831.45  5183.6 1829.94  5224.8 1830.69  5250.1 1832.00
  5286.2 1837.14  5291.4 1836.59  5327.6 1840.81  5332.7 1840.45  5368.9 1846.47
  5374.0 1845.81  5389.7 1848.45  5451.5 1850.40  5575.1 1856.40  5698.7 1856.92
#Mann=3,-1,0
  4042.6    0.05       0  4959.9    0.05       0  4972.4    0.05       0
Bank Sta=4959.9,4972.4
Exp/Cntr=0.3,0.1

Type RM Length L Ch R = 1,24814,150,150,150
BEGIN DESCRIPTION:
Elm 02 18 24813.93
END DESCRIPTION:
XS GIS Cut Line= 3
      1624885.47      6834663.38      1624913.69      6835247.12
      1624965.77      6835919.89
#Sta/Elev= 30
  4422.2 1836.74  4547.0 1831.91  4597.0 1828.32  4647.1 1826.28  4677.1 1827.86
  4757.2 1829.43  4877.3 1829.80  4917.4 1827.61  4937.4 1825.48  4967.5 1824.93
  4997.8 1823.40  4998.3 1822.90  5010.8 1822.90  5011.3 1823.40  5017.5 1824.26
  5047.6 1825.46  5067.7 1827.64  5117.8 1830.95  5198.1 1833.90  5248.2 1837.13
  5298.4 1839.28  5338.5 1840.30  5350.5 1841.20  5428.8 1842.54  5475.5 1842.12
  5480.5 1842.89  5509.0 1842.78  5579.2 1840.65  5619.3 1841.01  5681.4 1840.60
#Mann=3,-1,0
  4422.2    0.05       0  4997.8    0.05       0  5011.3    0.05       0
Bank Sta=4997.8,5011.3
Exp/Cntr=0.3,0.1

Type RM Length L Ch R = 1,24664,277,277,277
BEGIN DESCRIPTION:
Elm 02 18 24664.49
END DESCRIPTION:
XS GIS Cut Line= 3
      1624707.52      6834667.70      1624785.65      6835312.23
      1624792.15      6836043.25
#Sta/Elev= 30
  4354.2 1837.69  4535.8 1832.66  4586.2 1829.80  4616.4 1826.44  4636.6 1825.86
  4656.7 1826.86  4737.3 1828.44  4786.5 1828.11  4791.5 1828.70  4797.7 1828.10
  4908.5 1827.17  4948.8 1825.59  4955.2 1824.17  4969.0 1822.95  4982.4 1819.79
  4982.9 1819.29  4995.4 1819.29  4995.9 1819.79  4998.8 1820.99  5003.4 1820.99
  5019.2 1824.18  5029.2 1825.21  5089.2 1829.88  5119.2 1830.77  5269.2 1834.18
  5349.2 1835.11  5488.4 1835.00  5499.2 1835.78  5599.2 1834.60  5734.5 1837.99
#Mann=3,-1,0
  4354.2    0.05       0  4982.4    0.05       0  4995.9    0.05       0
Bank Sta=4982.4,4995.9
Exp/Cntr=0.3,0.1

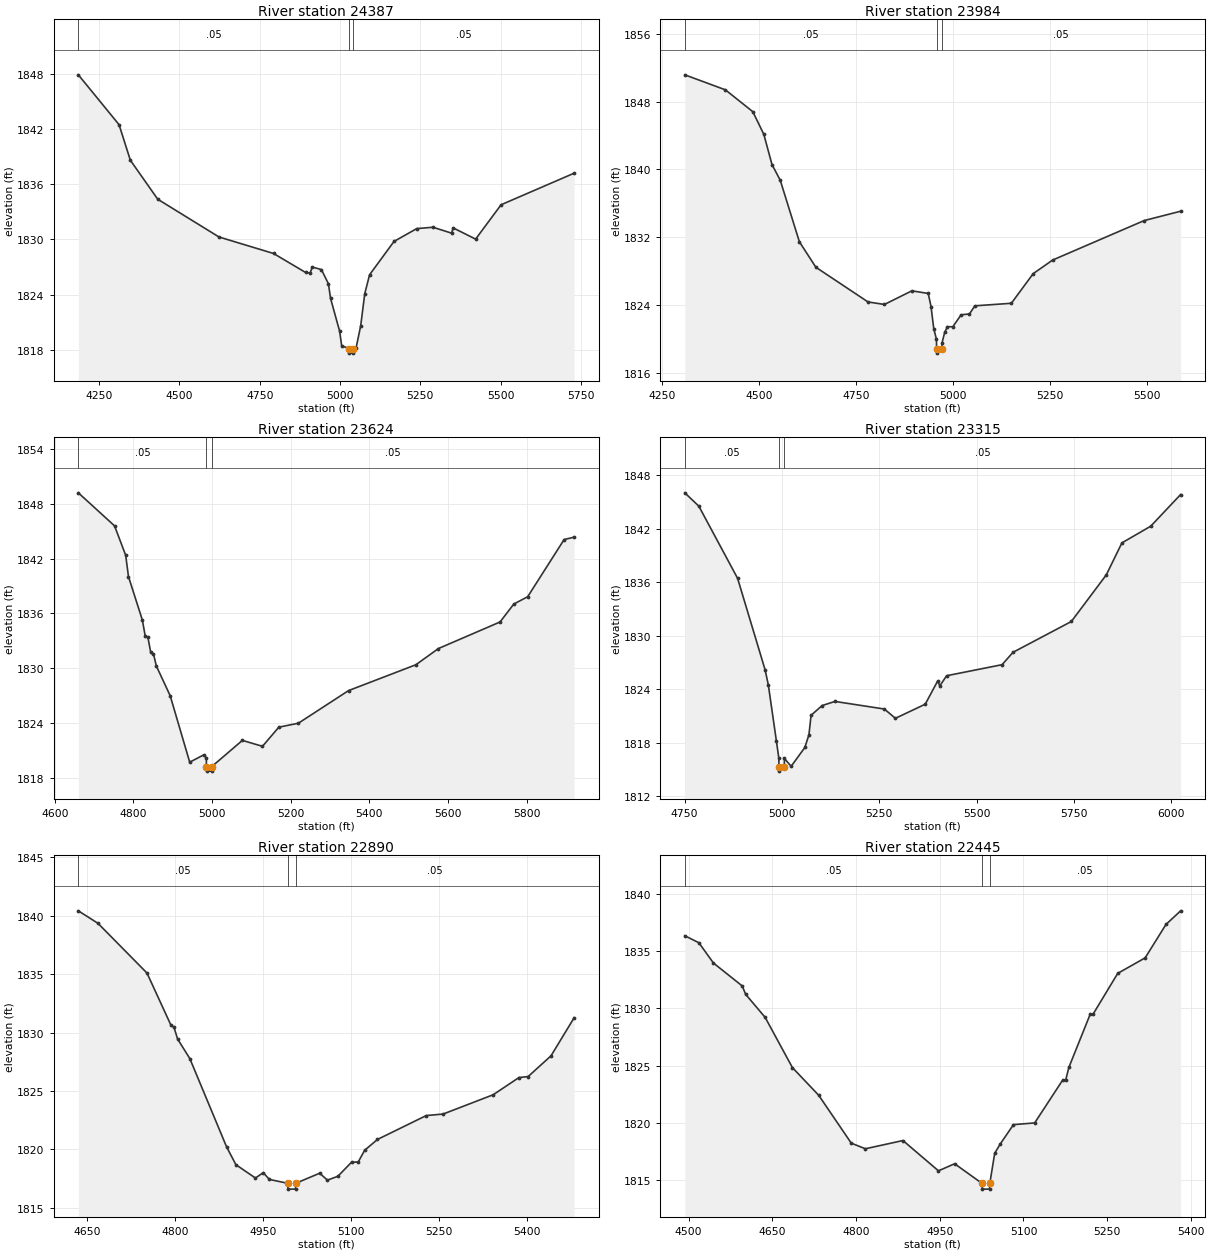
Type RM Length L Ch R = 1,24387,403,403,403
BEGIN DESCRIPTION:
Elm 02 18 24386.74
END DESCRIPTION:
XS GIS Cut Line= 4
      1624023.94      6834830.47      1624559.95      6835444.60
      1624640.25      6835563.96      1624724.86      6836143.22
#Sta/Elev= 30
  4184.9 1847.86  4311.7 1842.45  4346.9 1838.59  4432.3 1834.35  4623.1 1830.25
  4793.0 1828.46  4892.7 1826.40  4906.9 1826.34  4913.6 1826.99  4942.1 1826.71
  4963.9 1825.17  4970.5 1823.59  4999.0 1819.99  5005.1 1818.44  5028.4 1818.14
  5028.9 1817.64  5041.4 1817.64  5041.9 1818.14  5050.1 1818.21  5064.4 1820.61
  5077.1 1824.10  5092.1 1826.15  5168.2 1829.77  5238.9 1831.16  5289.5 1831.31
  5347.4 1830.67  5352.5 1831.24  5422.4 1830.02  5501.7 1833.75  5729.3 1837.18
#Mann=3,-1,0
  4184.9    0.05       0  5028.4    0.05       0  5041.9    0.05       0
Bank Sta=5028.4,5041.9
Exp/Cntr=0.3,0.1

Type RM Length L Ch R = 1,23984,360,360,360
BEGIN DESCRIPTION:
Elm 02 18 23983.57
END DESCRIPTION:
XS GIS Cut Line= 3
      1623815.60      6835249.30      1624299.54      6835744.08
      1624646.74      6836217.14
#Sta/Elev= 30
  4308.2 1851.15  4412.9 1849.38  4483.7 1846.80  4512.0 1844.13  4533.1 1840.57
  4554.4 1838.71  4603.8 1831.45  4646.3 1828.45  4780.7 1824.36  4823.1 1824.06
  4893.9 1825.67  4936.1 1825.36  4943.3 1823.82  4950.3 1821.22  4957.4 1819.94
  4957.6 1818.82  4958.1 1818.32  4971.2 1818.82  4971.6 1819.51  4978.6 1820.78
  4985.7 1821.44  4999.5 1821.43  5020.9 1822.84  5042.4 1822.94  5056.4 1823.90
  5150.5 1824.20  5206.9 1827.70  5257.0 1829.30  5493.2 1833.96  5587.1 1835.06
#Mann=3,-1,0
  4308.2    0.05       0  4957.6    0.05       0  4971.2    0.05       0
Bank Sta=4957.6,4971.2
Exp/Cntr=0.3,0.1

Type RM Length L Ch R = 1,23624,309,309,309
BEGIN DESCRIPTION:
Elm 02 18 23624.14
END DESCRIPTION:
XS GIS Cut Line= 3
      1623799.71      6835762.94      1624046.21      6835999.03
      1624760.77      6836578.31
#Sta/Elev= 30
  4660.0 1849.22  4752.1 1845.60  4780.4 1842.38  4787.6 1840.03  4822.8 1835.28
  4830.1 1833.54  4837.0 1833.37  4844.2 1831.72  4851.1 1831.57  4858.4 1830.24
  4893.6 1826.98  4943.3 1819.69  4978.5 1820.48  4985.7 1820.18  4985.8 1819.21
  4986.3 1818.71  4999.0 1818.71  4999.5 1819.21  5077.3 1822.08  5128.4 1821.43
  5170.0 1823.53  5219.6 1823.96  5347.4 1827.54  5518.5 1830.37  5576.0 1832.15
  5732.6 1835.06  5767.8 1837.03  5803.0 1837.83  5895.7 1844.10  5921.2 1844.36
#Mann=3,-1,0
  4660.0    0.05       0  4985.8    0.05       0  4999.5    0.05       0
Bank Sta=4985.8,4999.5
Exp/Cntr=0.3,0.1

Type RM Length L Ch R = 1,23315,425,425,425
BEGIN DESCRIPTION:
Elm 02 18 23315.33
END DESCRIPTION:
XS GIS Cut Line= 3
      1623705.91      6836037.19      1623858.71      6836235.14
      1624292.73      6837162.21
#Sta/Elev= 30
  4750.5 1846.03  4786.5 1844.54  4886.1 1836.45  4956.8 1826.19  4965.0 1824.52
  4985.8 1818.22  4992.1 1816.28  4992.4 1815.34  4992.9 1814.84  5006.1 1815.34
  5006.4 1816.26  5023.7 1815.38  5058.9 1817.49  5069.4 1818.92  5074.9 1821.10
  5103.3 1822.19  5136.2 1822.65  5263.1 1821.80  5291.5 1820.76  5368.1 1822.34
  5400.1 1824.94  5405.6 1824.39  5423.0 1825.53  5565.5 1826.77  5593.8 1828.16
  5743.5 1831.61  5833.2 1836.83  5873.4 1840.42  5947.4 1842.29  6024.2 1845.84
#Mann=3,-1,0
  4750.5    0.05       0  4992.4    0.05       0  5006.1    0.05       0
Bank Sta=4992.4,5006.1
Exp/Cntr=0.3,0.1

Type RM Length L Ch R = 1,22890,445,445,445
BEGIN DESCRIPTION:
Elm 02 18 22889.76
END DESCRIPTION:
XS GIS Cut Line= 3
      1623524.33      6836215.87      1623627.20      6836566.13
      1623822.08      6837003.97
#Sta/Elev= 30
  4635.7 1840.41  4669.2 1839.34  4752.6 1835.09  4793.4 1830.63  4798.6 1830.45
  4804.7 1829.45  4825.5 1827.78  4888.1 1820.23  4904.0 1818.70  4937.3 1817.56
  4950.6 1818.02  4961.0 1817.44  4992.3 1817.11  4992.8 1816.61  5005.5 1816.61
  5006.0 1817.11  5046.6 1817.97  5059.9 1817.38  5077.7 1817.71  5100.9 1818.91
  5112.3 1818.93  5123.2 1819.93  5145.1 1820.86  5228.1 1822.90  5256.8 1823.03
  5342.1 1824.68  5385.9 1826.15  5401.7 1826.24  5440.6 1828.01  5480.0 1831.27
#Mann=3,-1,0
  4635.7    0.05       0  4992.3    0.05       0  5006.0    0.05       0
Bank Sta=4992.3,5006
Exp/Cntr=0.3,0.1

Type RM Length L Ch R = 1,22445,417,417,417
BEGIN DESCRIPTION:
Elm 02 18 22444.92
END DESCRIPTION:
XS GIS Cut Line= 3
      1623194.19      6836348.00      1623313.97      6836844.49
      1623393.70      6837213.64
#Sta/Elev= 30
  4493.2 1836.35  4518.4 1835.74  4544.6 1833.96  4596.1 1831.96  4602.2 1831.23
  4637.2 1829.21  4686.0 1824.82  4733.1 1822.40  4791.5 1818.21  4816.8 1817.72
  4884.1 1818.44  4947.7 1815.79  4976.7 1816.41  5025.8 1814.69  5026.3 1814.19
  5039.2 1814.19  5039.7 1814.69  5048.5 1817.33  5058.7 1818.16  5082.1 1819.83
  5120.1 1819.98  5170.3 1823.73  5175.5 1823.70  5181.4 1824.84  5219.6 1829.49
  5224.7 1829.49  5268.9 1833.06  5318.1 1834.42  5355.4 1837.34  5381.6 1838.53
#Mann=3,-1,0
  4493.2    0.05       0  5025.8    0.05       0  5039.7    0.05       0
Bank Sta=5025.8,5039.7
Exp/Cntr=0.3,0.1

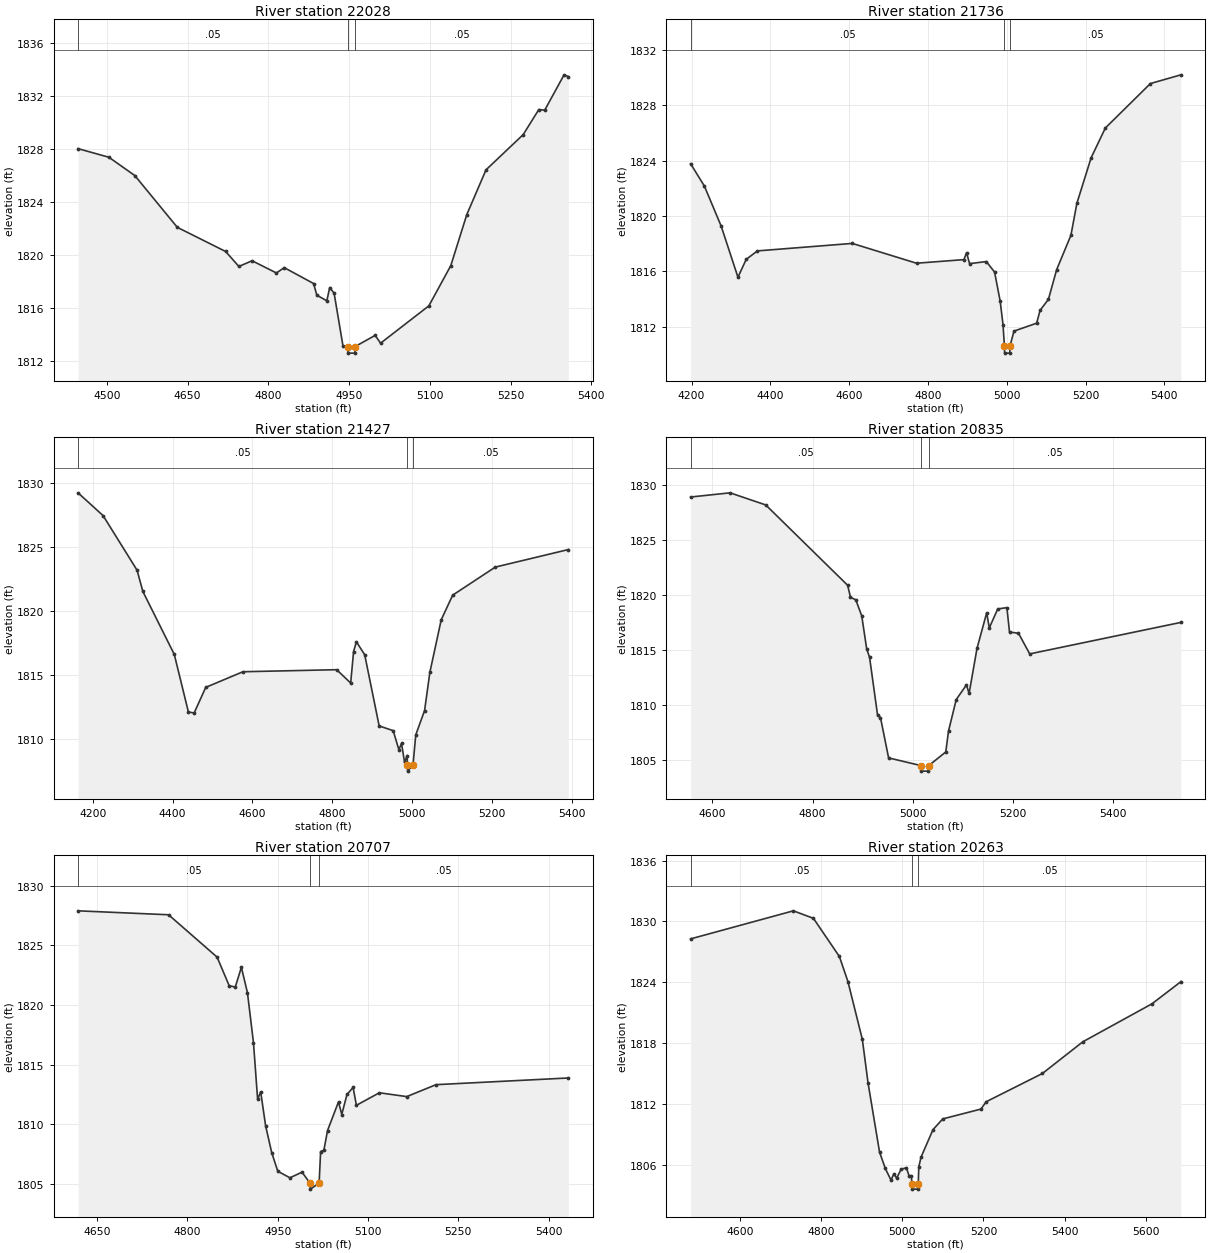
Type RM Length L Ch R = 1,22028,292,292,292
BEGIN DESCRIPTION:
Elm 02 18 22028.04
END DESCRIPTION:
XS GIS Cut Line= 3
      1622721.97      6836404.57      1622923.35      6836923.65
      1623063.98      6837248.33
#Sta/Elev= 30
  4446.7 1828.03  4504.0 1827.38  4552.1 1826.00  4631.1 1822.09  4720.8 1820.27
  4745.4 1819.14  4769.9 1819.57  4815.1 1818.65  4829.7 1819.05  4884.2 1817.85
  4890.2 1816.97  4908.8 1816.55  4914.1 1817.55  4922.3 1817.12  4938.7 1813.16
  4947.6 1813.10  4948.1 1812.60  4961.0 1812.60  4961.5 1813.10  4998.5 1813.94
  5008.6 1813.35  5098.3 1816.17  5139.0 1819.20  5168.7 1823.05  5204.4 1826.43
  5273.5 1829.09  5302.5 1830.98  5313.4 1830.93  5349.4 1833.60  5357.3 1833.47
#Mann=3,-1,0
  4446.7    0.05       0  4947.6    0.03       0  4961.5    0.05       0
Bank Sta=4947.6,4961.5
Exp/Cntr=0.3,0.1

Type RM Length L Ch R = 1,21736,309,309,309
BEGIN DESCRIPTION:
Elm 02 18 21736.09
END DESCRIPTION:
XS GIS Cut Line= 3
      1622117.79      6836395.87      1622654.25      6836998.31
      1622895.05      6837363.84
#Sta/Elev= 30
  4197.7 1823.77  4232.6 1822.16  4275.2 1819.27  4317.8 1815.58  4338.8 1816.87
  4367.2 1817.48  4608.0 1818.02  4771.0 1816.59  4891.4 1816.85  4898.1 1817.35
  4905.7 1816.56  4948.3 1816.71  4969.2 1815.95  4983.4 1813.85  4990.6 1812.15
  4994.2 1810.60  4994.7 1810.10  5007.7 1810.10  5008.2 1810.60  5018.4 1811.69
  5075.9 1812.26  5084.7 1813.19  5105.8 1813.98  5126.8 1816.13  5163.0 1818.61
  5178.0 1820.91  5214.2 1824.20  5250.3 1826.35  5364.7 1829.56  5442.1 1830.19
#Mann=3,-1,0
  4197.7    0.05       0  4994.2    0.05       0  5008.2    0.05       0
Bank Sta=4994.2,5008.2
Exp/Cntr=0.3,0.1

Type RM Length L Ch R = 1,21427,592,592,592
BEGIN DESCRIPTION:
Elm 02 18 21426.89
END DESCRIPTION:
XS GIS Cut Line= 4
      1621779.28      6836635.48      1622275.78      6837022.61
      1622412.93      6837180.60      1622710.74      6837429.92
#Sta/Elev= 30
  4163.5 1829.25  4226.2 1827.47  4311.2 1823.21  4325.7 1821.55  4404.4 1816.63
  4439.7 1812.14  4454.1 1812.06  4483.1 1814.06  4576.2 1815.28  4810.8 1815.44
  4845.9 1814.40  4853.2 1816.86  4860.2 1817.62  4881.0 1816.61  4917.2 1811.05
  4952.3 1810.68  4966.5 1809.20  4973.2 1809.68  4980.8 1808.21  4987.4 1808.74
  4988.0 1808.02  4988.5 1807.52  5002.0 1808.02  5008.8 1810.35  5030.9 1812.25
  5044.1 1815.23  5072.5 1819.33  5101.2 1821.26  5207.9 1823.45  5390.7 1824.82
#Mann=3,-1,0
  4163.5    0.05       0  4988.0    0.05       0  5002.0    0.05       0
Bank Sta=4988,5002
Exp/Cntr=0.3,0.1

Type RM Length L Ch R = 1,20835,128,128,128
BEGIN DESCRIPTION:
Elm 02 18 20835.09
END DESCRIPTION:
XS GIS Cut Line= 4
      1621515.35      6837123.05      1621904.28      6837334.88
      1621970.25      6837362.66      1622418.20      6837480.72
#Sta/Elev= 30
  4556.9 1828.89  4635.5 1829.27  4706.7 1828.17  4870.0 1820.88  4875.7 1819.79
  4886.2 1819.56  4898.1 1818.11  4908.0 1815.10  4913.7 1814.35  4929.8 1809.06
  4935.5 1808.87  4951.7 1805.21  5016.6 1804.51  5017.1 1804.01  5031.2 1804.01
  5031.7 1804.51  5065.7 1805.75  5071.2 1807.66  5086.6 1810.51  5107.0 1811.84
  5112.2 1811.06  5128.0 1815.15  5147.3 1818.38  5152.5 1817.01  5169.3 1818.73
  5187.6 1818.85  5192.8 1816.63  5210.7 1816.53  5233.1 1814.65  5534.6 1817.51
#Mann=3,-1,0
  4556.9    0.05       0  5016.6    0.05       0  5031.7    0.05       0
Bank Sta=5016.6,5031.7
Exp/Cntr=0.3,0.1

Type RM Length L Ch R = 1,20707,444,444,444
BEGIN DESCRIPTION:
Elm 02 18 20706.61
END DESCRIPTION:
XS GIS Cut Line= 3
      1621525.83      6837414.75      1621904.28      6837463.35
      1622306.92      6837623.02
#Sta/Elev= 30
  4618.2 1827.89  4768.6 1827.56  4849.3 1824.01  4869.4 1821.61  4879.5 1821.51
  4889.6 1823.16  4899.7 1821.03  4909.7 1816.85  4916.6 1812.10  4921.7 1812.73
  4929.9 1809.88  4940.0 1807.64  4950.1 1806.08  4970.2 1805.53  4990.4 1806.00
  5003.7 1805.08  5004.2 1804.58  5018.8 1805.08  5021.3 1807.73  5026.7 1807.84
  5032.8 1809.49  5051.0 1811.89  5056.4 1810.83  5065.1 1812.51  5075.3 1813.10
  5080.7 1811.60  5118.9 1812.65  5164.4 1812.33  5213.1 1813.33  5432.9 1813.89
#Mann=3,-1,0
  4618.2    0.05       0  5003.7    0.05       0  5018.8    0.05       0
Bank Sta=5003.7,5018.8
Exp/Cntr=0.3,0.1

Type RM Length L Ch R = 1,20263,490,490,490
BEGIN DESCRIPTION:
Elm 02 18 20263.34
END DESCRIPTION:
XS GIS Cut Line= 3
      1621751.25      6838171.94      1622122.80      6837810.81
      1622760.89      6837550.72
#Sta/Elev= 30
  4479.0 1828.29  4732.0 1831.05  4781.4 1830.31  4845.2 1826.56  4866.3 1824.09
  4901.8 1818.40  4915.9 1814.10  4944.2 1807.30  4958.3 1805.70  4972.3 1804.55
  4979.5 1805.17  4986.4 1804.74  4997.1 1805.61  5010.3 1805.77  5016.8 1804.97
  5022.2 1804.98  5024.3 1804.16  5024.8 1803.66  5039.0 1803.66  5039.5 1804.16
  5040.8 1805.84  5046.2 1806.79  5075.7 1809.51  5099.7 1810.57  5193.9 1811.54
  5206.7 1812.26  5345.1 1815.04  5444.7 1818.16  5615.0 1821.90  5686.2 1824.08
#Mann=3,-1,0
  4479.0    0.05       0  5024.3    0.05       0  5039.5    0.05       0
Bank Sta=5024.3,5039.5
Exp/Cntr=0.3,0.1