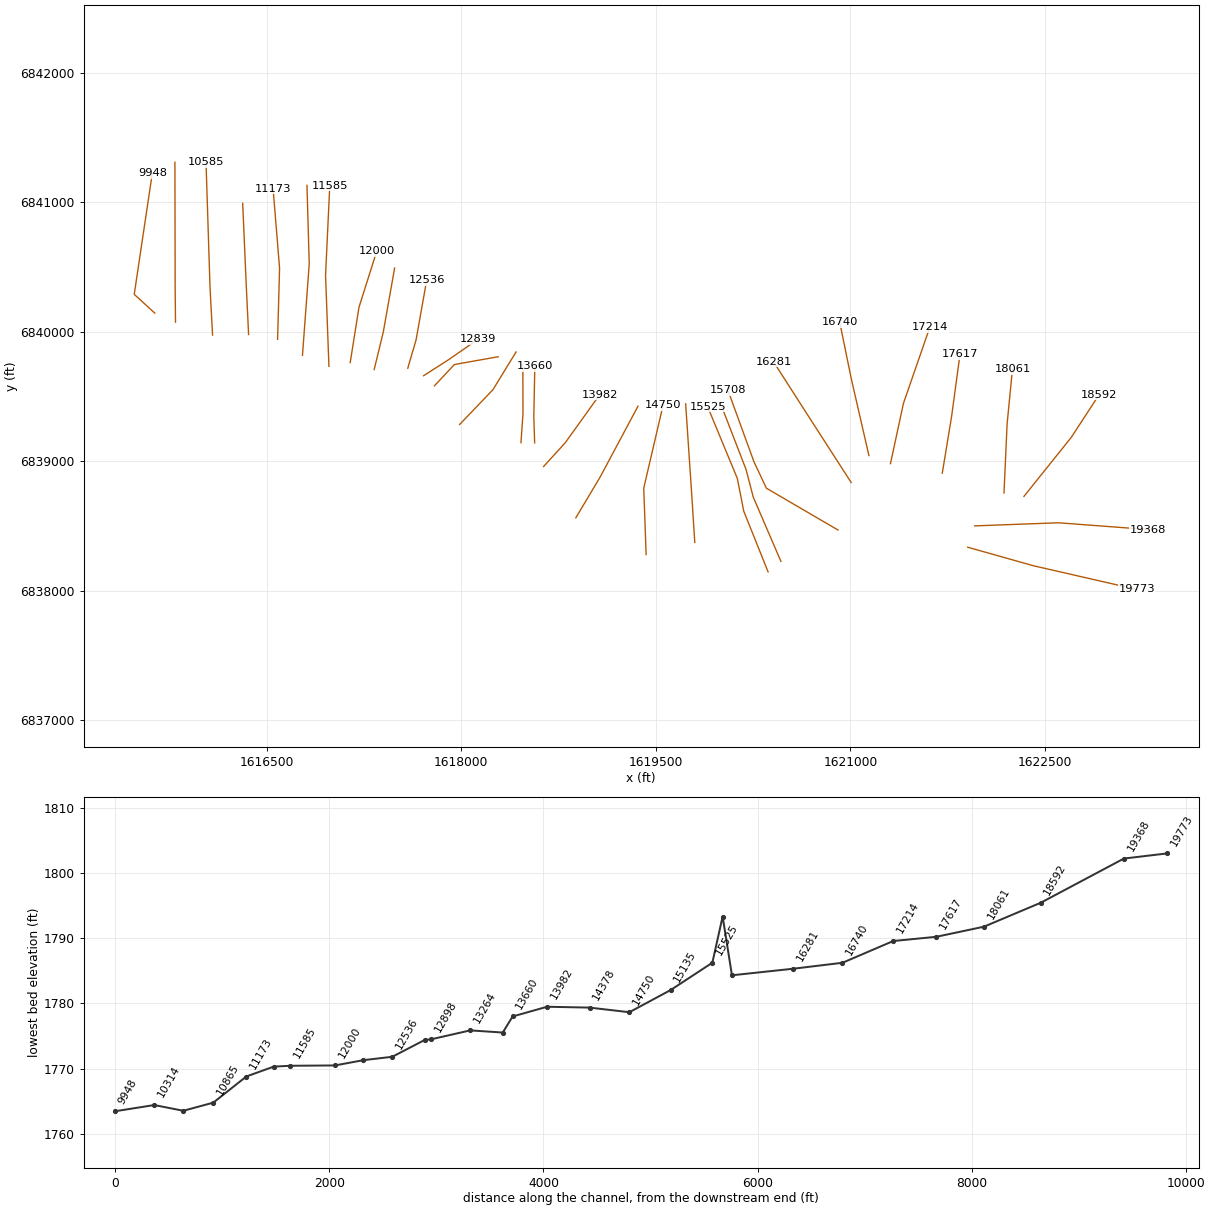
HEC-RAS study Elm 02 18.prj: Elm 02 18 Base Level Engineering

--- Elm 02 18.g01 (geometry) --- (continued)

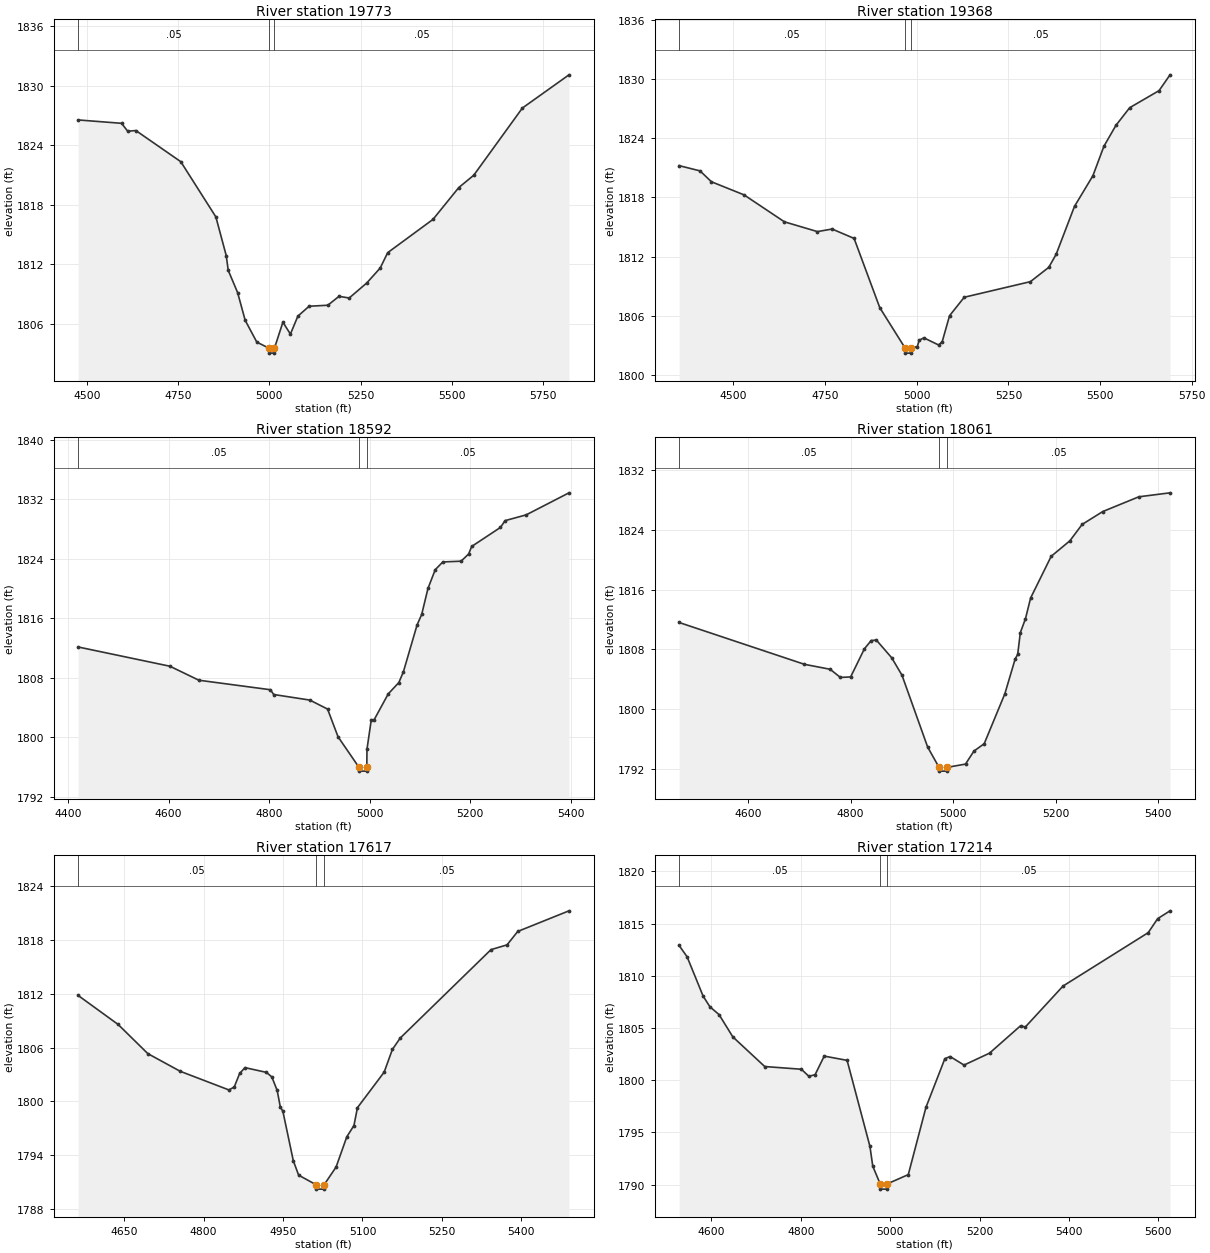
Type RM Length L Ch R = 1,19773,405,405,405
BEGIN DESCRIPTION:
Elm 02 18 19773.3
END DESCRIPTION:
XS GIS Cut Line= 3
      1621904.06      6838335.11      1622407.52      6838192.75
      1623209.58      6838008.73
#Sta/Elev= 30
  4475.4 1826.54  4594.6 1826.20  4611.5 1825.40  4633.8 1825.47  4757.0 1822.33
  4853.2 1816.76  4881.7 1812.85  4887.1 1811.37  4912.8 1809.13  4933.6 1806.33
  4965.5 1804.13  4998.7 1803.52  4999.2 1803.02  5013.4 1803.02  5013.9 1803.52
  5037.0 1806.14  5057.6 1804.94  5078.1 1806.75  5108.9 1807.75  5160.2 1807.85
  5190.9 1808.75  5218.8 1808.58  5266.8 1810.09  5303.8 1811.60  5324.3 1813.15
  5448.6 1816.51  5519.3 1819.72  5560.3 1820.96  5693.7 1827.74  5821.5 1831.09
#Mann=3,-1,0
  4475.4    0.05       0  4998.7    0.05       0  5013.9    0.05       0
Bank Sta=4998.7,5013.9
Exp/Cntr=0.3,0.1

Type RM Length L Ch R = 1,19368,776,776,776
BEGIN DESCRIPTION:
Elm 02 18 19368.2
END DESCRIPTION:
XS GIS Cut Line= 3
      1621958.03      6838499.90      1622604.72      6838523.77
      1623294.82      6838471.69
#Sta/Elev= 30
  4351.8 1821.22  4408.8 1820.69  4439.8 1819.59  4528.9 1818.26  4639.0 1815.53
  4729.0 1814.54  4769.1 1814.80  4829.1 1813.85  4899.1 1806.84  4968.5 1802.73
  4969.0 1802.23  4983.3 1802.23  4983.8 1802.73  5001.6 1802.90  5006.7 1803.53
  5019.3 1803.78  5059.4 1803.06  5069.4 1803.38  5089.5 1806.02  5129.6 1807.89
  5310.1 1809.47  5360.2 1810.92  5380.3 1812.24  5430.4 1817.10  5480.6 1820.20
  5510.7 1823.19  5543.2 1825.29  5580.9 1827.09  5661.1 1828.82  5691.0 1830.42
#Mann=3,-1,0
  4351.8    0.05       0  4968.5    0.05       0  4983.8    0.05       0
Bank Sta=4968.5,4983.8
Exp/Cntr=0.3,0.1

Type RM Length L Ch R = 1,18592,531,531,531
BEGIN DESCRIPTION:
Elm 02 18 18592.24
END DESCRIPTION:
XS GIS Cut Line= 3
      1622337.79      6838727.76      1622702.37      6839183.49
      1622917.12      6839513.21
#Sta/Elev= 30
  4419.7 1812.14  4602.5 1809.55  4660.1 1807.67  4802.6 1806.39  4809.0 1805.75
  4881.0 1805.00  4916.3 1803.79  4937.1 1800.07  4978.9 1795.95  4979.4 1795.45
  4993.9 1795.45  4994.4 1795.95  4994.7 1798.38  5003.3 1802.36  5009.0 1802.36
  5037.1 1805.84  5058.2 1807.36  5067.3 1808.82  5094.4 1815.09  5103.6 1816.51
  5116.1 1820.00  5130.6 1822.53  5145.7 1823.57  5182.0 1823.67  5197.1 1824.64
  5203.1 1825.65  5260.4 1828.21  5269.6 1829.12  5311.7 1829.90  5396.8 1832.86
#Mann=3,-1,0
  4419.7    0.05       0  4978.9    0.05       0  4994.4    0.05       0
Bank Sta=4978.9,4994.4
Exp/Cntr=0.3,0.1

Type RM Length L Ch R = 1,18061,444,444,444
BEGIN DESCRIPTION:
Elm 02 18 18061.25
END DESCRIPTION:
XS GIS Cut Line= 3
      1622183.71      6838753.80      1622207.58      6839285.49
      1622248.81      6839708.66
#Sta/Elev= 30
  4465.5 1811.60  4709.9 1806.02  4760.0 1805.36  4780.0 1804.27  4800.0 1804.34
  4826.9 1808.10  4840.1 1809.19  4850.1 1809.26  4880.1 1806.89  4900.1 1804.57
  4950.2 1794.98  4972.4 1792.27  4972.9 1791.77  4987.5 1791.77  4988.0 1792.27
  5024.0 1792.71  5040.4 1794.44  5060.5 1795.43  5100.7 1802.08  5120.8 1806.72
  5125.8 1807.35  5130.9 1810.24  5140.9 1812.09  5151.0 1814.87  5191.1 1820.43
  5227.6 1822.50  5251.4 1824.68  5291.6 1826.40  5362.0 1828.37  5422.9 1828.90
#Mann=3,-1,0
  4465.5    0.05       0  4972.4    0.05       0  4988.0    0.05       0
Bank Sta=4972.4,4988
Exp/Cntr=0.3,0.1

Type RM Length L Ch R = 1,17617,403,403,403
BEGIN DESCRIPTION:
Elm 02 18 17616.67
END DESCRIPTION:
XS GIS Cut Line= 3
      1621708.01      6838906.88      1621779.63      6839343.07
      1621844.61      6839823.97
#Sta/Elev= 30
  4562.8 1811.84  4638.4 1808.60  4694.6 1805.34  4755.8 1803.37  4847.7 1801.29
  4857.8 1801.62  4868.0 1803.13  4878.1 1803.78  4918.6 1803.25  4928.8 1802.74
  4938.9 1801.23  4944.7 1799.42  4949.7 1798.89  4969.3 1793.40  4979.4 1791.78
  5012.1 1790.72  5012.6 1790.22  5027.2 1790.22  5027.7 1790.72  5050.2 1792.69
  5070.4 1796.06  5083.9 1797.32  5090.5 1799.31  5141.0 1803.28  5156.5 1805.81
  5171.3 1807.08  5342.8 1816.95  5373.1 1817.48  5393.3 1818.98  5490.1 1821.28
#Mann=3,-1,0
  4562.8    0.05       0  5012.1    0.05       0  5027.7    0.05       0
Bank Sta=5012.1,5027.7
Exp/Cntr=0.3,0.1

Type RM Length L Ch R = 1,17214,474,474,474
BEGIN DESCRIPTION:
Elm 02 18 17214.08
END DESCRIPTION:
XS GIS Cut Line= 3
      1621308.70      6838980.63      1621408.53      6839445.07
      1621612.11      6840034.13
#Sta/Elev= 30
  4527.7 1812.90  4545.5 1811.82  4581.4 1808.05  4596.6 1807.03  4617.1 1806.28
  4647.8 1804.15  4719.2 1801.31  4801.2 1801.05  4818.0 1800.37  4831.9 1800.53
  4852.3 1802.31  4903.5 1801.90  4954.6 1793.66  4960.9 1791.77  4977.5 1790.07
  4978.0 1789.57  4992.6 1789.57  4993.1 1790.07  5040.4 1790.96  5079.9 1797.40
  5122.2 1802.06  5133.9 1802.27  5165.1 1801.45  5222.1 1802.59  5291.5 1805.21
  5302.1 1805.09  5386.7 1809.02  5577.2 1814.13  5598.3 1815.47  5626.0 1816.22
#Mann=3,-1,0
  4527.7    0.05       0  4977.5    0.05       0  4993.1    0.05       0
Bank Sta=4977.5,4993.1
Exp/Cntr=0.3,0.1

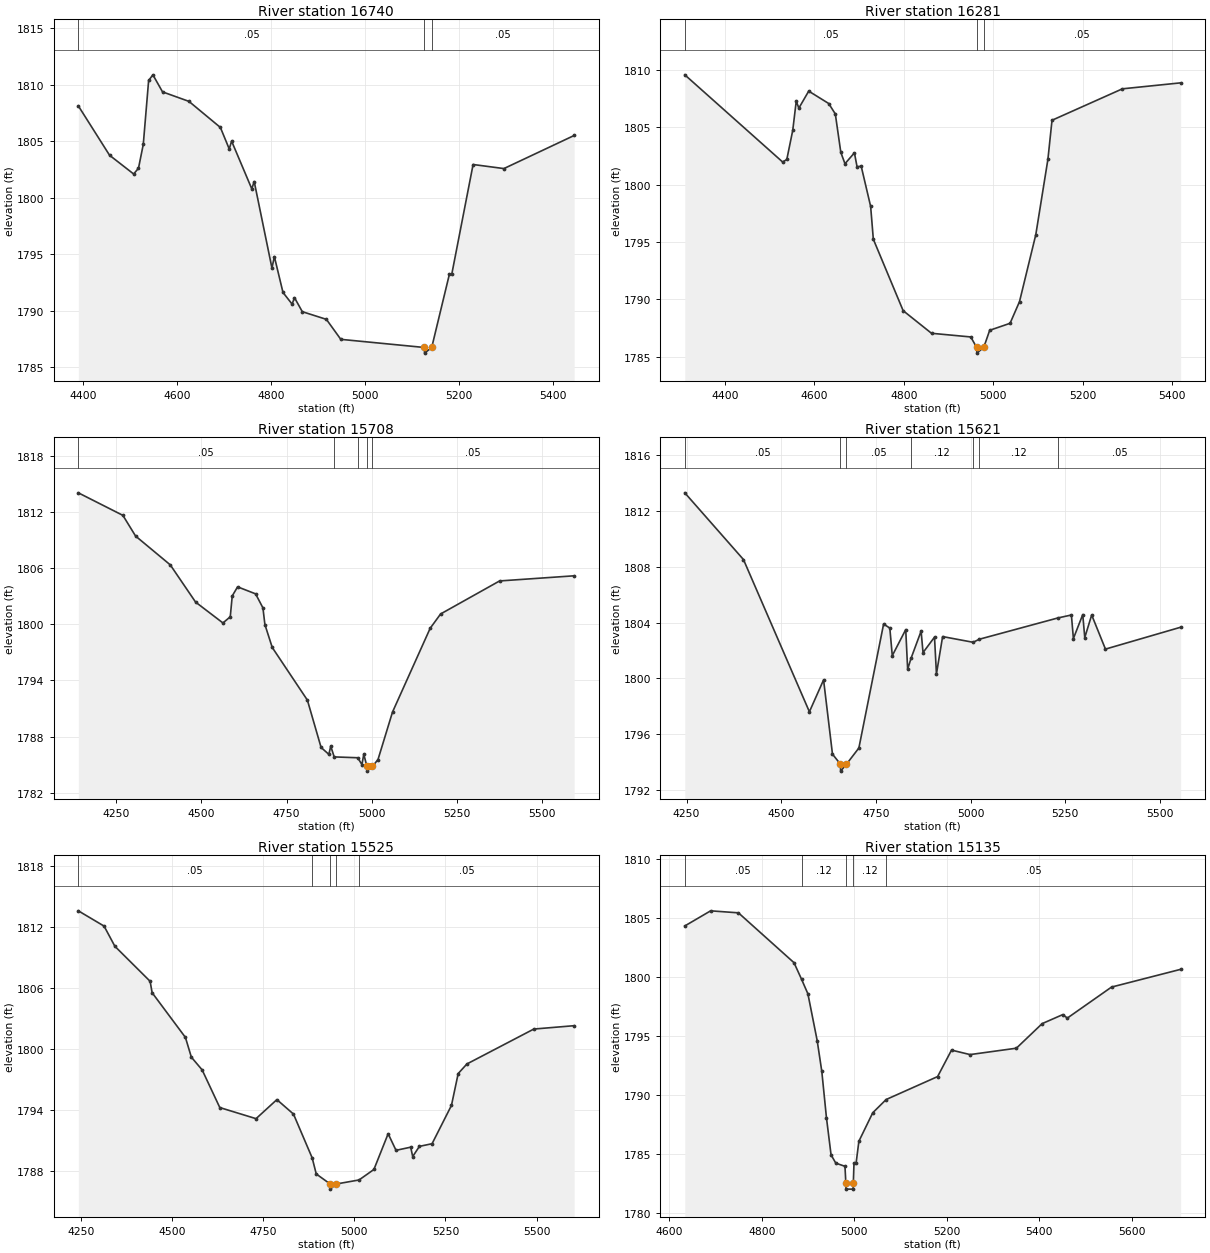
Type RM Length L Ch R = 1,16740,459,459,459
BEGIN DESCRIPTION:
Elm 02 18 16740.08
END DESCRIPTION:
XS GIS Cut Line= 3
      1621142.52      6839043.18      1621005.79      6839640.02
      1620917.15      6840074.57
#Sta/Elev= 30
  4389.7 1808.12  4456.2 1803.75  4507.5 1802.09  4517.8 1802.60  4528.0 1804.71
  4539.4 1810.37  4548.5 1810.87  4569.0 1809.36  4625.2 1808.52  4692.2 1806.21
  4711.0 1804.31  4716.1 1805.00  4759.0 1800.78  4764.2 1801.42  4802.0 1793.76
  4807.1 1794.78  4825.5 1791.60  4844.9 1790.57  4850.0 1791.14  4866.6 1789.90
  4917.9 1789.22  4948.6 1787.45  5126.5 1786.73  5127.0 1786.23  5142.2 1786.73
  5179.8 1793.21  5184.9 1793.22  5230.3 1802.93  5295.9 1802.57  5445.5 1805.50
#Mann=3,-1,0
  4389.7    0.05       0  5126.5    0.03       0  5142.2    0.05       0
Bank Sta=5126.5,5142.2
Exp/Cntr=0.3,0.1

Type RM Length L Ch R = 1,16281,573,573,573
BEGIN DESCRIPTION:
Elm 02 18 16281.45
END DESCRIPTION:
XS GIS Cut Line= 3
      1621005.77      6838834.93      1620630.36      6839418.66
      1620406.84      6839768.05
#Sta/Elev= 30
  4310.2 1809.58  4529.0 1801.98  4538.3 1802.20  4551.6 1804.74  4559.4 1807.28
  4565.3 1806.68  4587.3 1808.16  4632.0 1807.08  4646.8 1806.17  4659.1 1802.82
  4668.4 1801.83  4689.5 1802.78  4695.4 1801.57  4704.7 1801.61  4725.8 1798.11
  4731.8 1795.25  4798.5 1789.02  4861.9 1787.05  4949.7 1786.73  4962.8 1785.82
  4963.3 1785.32  4978.8 1785.82  4992.0 1787.31  5037.6 1787.92  5058.7 1789.81
  5095.1 1795.64  5122.2 1802.21  5131.4 1805.62  5288.8 1808.36  5419.0 1808.88
#Mann=3,-1,0
  4310.2    0.05       0  4962.8    0.03       0  4978.8    0.05       0
Bank Sta=4962.8,4978.8
Exp/Cntr=0.3,0.1

Type RM Length L Ch R = 1,15708,87,87,87
BEGIN DESCRIPTION:
Elm 02 18 15707.62
END DESCRIPTION:
XS GIS Cut Line= 4
      1620904.39      6838467.91      1620352.27      6838790.84
      1620255.92      6838996.57      1620055.39      6839548.68
#Sta/Elev= 30
  4139.3 1814.06  4270.0 1811.65  4307.2 1809.44  4408.9 1806.36  4483.2 1802.38
  4563.4 1800.15  4584.9 1800.81  4590.7 1803.04  4606.4 1804.01  4659.2 1803.26
  4680.7 1801.76  4686.5 1799.98  4708.0 1797.53  4811.1 1791.90  4851.3 1786.84
  4874.1 1786.10  4879.6 1786.98  4889.7 1785.83  4958.7 1785.74  4971.0 1785.01
  4976.5 1786.11  4985.8 1784.81  4986.3 1784.31  5001.8 1784.81  5018.2 1785.55
  5060.8 1790.63  5171.2 1799.58  5201.8 1801.11  5374.8 1804.64  5593.5 1805.19
#Mann=5,-1,0
  4139.3    0.05       0  4889.7    0.12       0  4958.7    0.05       0
  4985.8    0.03       0  5001.8    0.05       0
Bank Sta=4985.8,5001.8
Exp/Cntr=0.3,0.1

Type RM Length L Ch R = 1,15621,96,96,96
BEGIN DESCRIPTION:
Elm 02 18 15620.84
END DESCRIPTION:
XS GIS Cut Line= 4
      1620464.27      6838225.70      1620250.71      6838723.13
      1620196.02      6838934.07      1619998.11      6839447.07
#Sta/Elev= 30
  4245.3 1813.31  4400.2 1808.52  4574.3 1797.59  4611.7 1799.88  4635.2 1794.55
  4656.2 1793.83  4656.7 1793.33  4672.2 1793.83  4704.9 1794.99  4770.2 1803.89
  4786.6 1803.60  4793.1 1801.62  4828.6 1803.49  4833.7 1800.64  4842.5 1801.42
  4869.2 1803.38  4874.3 1801.84  4904.6 1802.95  4909.7 1800.31  4926.0 1802.99
  5006.5 1802.58  5023.0 1802.80  5230.8 1804.33  5266.0 1804.54  5271.3 1802.85
  5296.0 1804.57  5301.3 1802.92  5319.6 1804.54  5355.9 1802.09  5554.4 1803.66
#Mann=7,-1,0
  4245.3    0.05       0  4656.2    0.07       0  4672.2    0.05       0
  4842.5    0.12       0  5006.5    0.05       0  5023.0    0.12       0
  5230.8    0.05       0
Bank Sta=4656.2,4672.2
Exp/Cntr=0.3,0.1

Type RM Length L Ch R = 1,15525,390,390,390
BEGIN DESCRIPTION:
Elm 02 18 15524.99
END DESCRIPTION:
XS GIS Cut Line= 4
      1620365.29      6838145.01      1620177.79      6838613.76
      1620128.32      6838866.36      1619899.58      6839420.01
#Sta/Elev= 30
  4242.0 1813.57  4312.7 1812.07  4342.3 1810.09  4439.1 1806.65  4444.6 1805.53
  4536.0 1801.14  4552.3 1799.20  4581.9 1797.95  4630.4 1794.25  4729.9 1793.16
  4787.1 1795.03  4832.7 1793.61  4884.0 1789.31  4895.2 1787.73  4933.6 1786.74
  4934.1 1786.24  4949.6 1786.74  5012.7 1787.14  5053.5 1788.17  5092.6 1791.68
  5114.2 1790.05  5154.5 1790.36  5160.0 1789.44  5178.5 1790.44  5213.2 1790.70
  5266.4 1794.46  5284.9 1797.59  5308.8 1798.53  5492.5 1801.96  5603.3 1802.29
#Mann=5,-1,0
  4242.0    0.05       0  4884.0    0.12       0  4933.6    0.07       0
  4949.6    0.12       0  5012.7    0.05       0
Bank Sta=4933.6,4949.6
Exp/Cntr=0.3,0.1

Type RM Length L Ch R = 1,15135,385,385,385
BEGIN DESCRIPTION:
Elm 02 18 15135.15
END DESCRIPTION:
XS GIS Cut Line= 3
      1619800.35      6838372.20      1619776.92      6838742.01
      1619730.04      6839442.49
#Sta/Elev= 30
  4633.6 1804.30  4689.5 1805.58  4749.6 1805.41  4869.9 1801.19  4886.2 1799.79
  4899.9 1798.56  4920.0 1794.60  4930.0 1791.99  4940.0 1788.09  4950.0 1784.94
  4960.2 1784.24  4980.1 1783.97  4982.0 1782.54  4982.5 1782.04  4997.7 1782.04
  4998.2 1782.54  4999.6 1784.25  5004.2 1784.25  5010.2 1786.09  5040.2 1788.50
  5069.2 1789.62  5180.5 1791.56  5210.6 1793.80  5250.7 1793.42  5350.9 1793.96
  5406.7 1796.04  5451.1 1796.80  5461.2 1796.51  5556.7 1799.13  5706.2 1800.63
#Mann=5,-1,0
  4633.6    0.05       0  4886.2    0.12       0  4982.0    0.07       0
  4998.2    0.12       0  5069.2    0.05       0
Bank Sta=4982,4998.2
Exp/Cntr=0.3,0.1

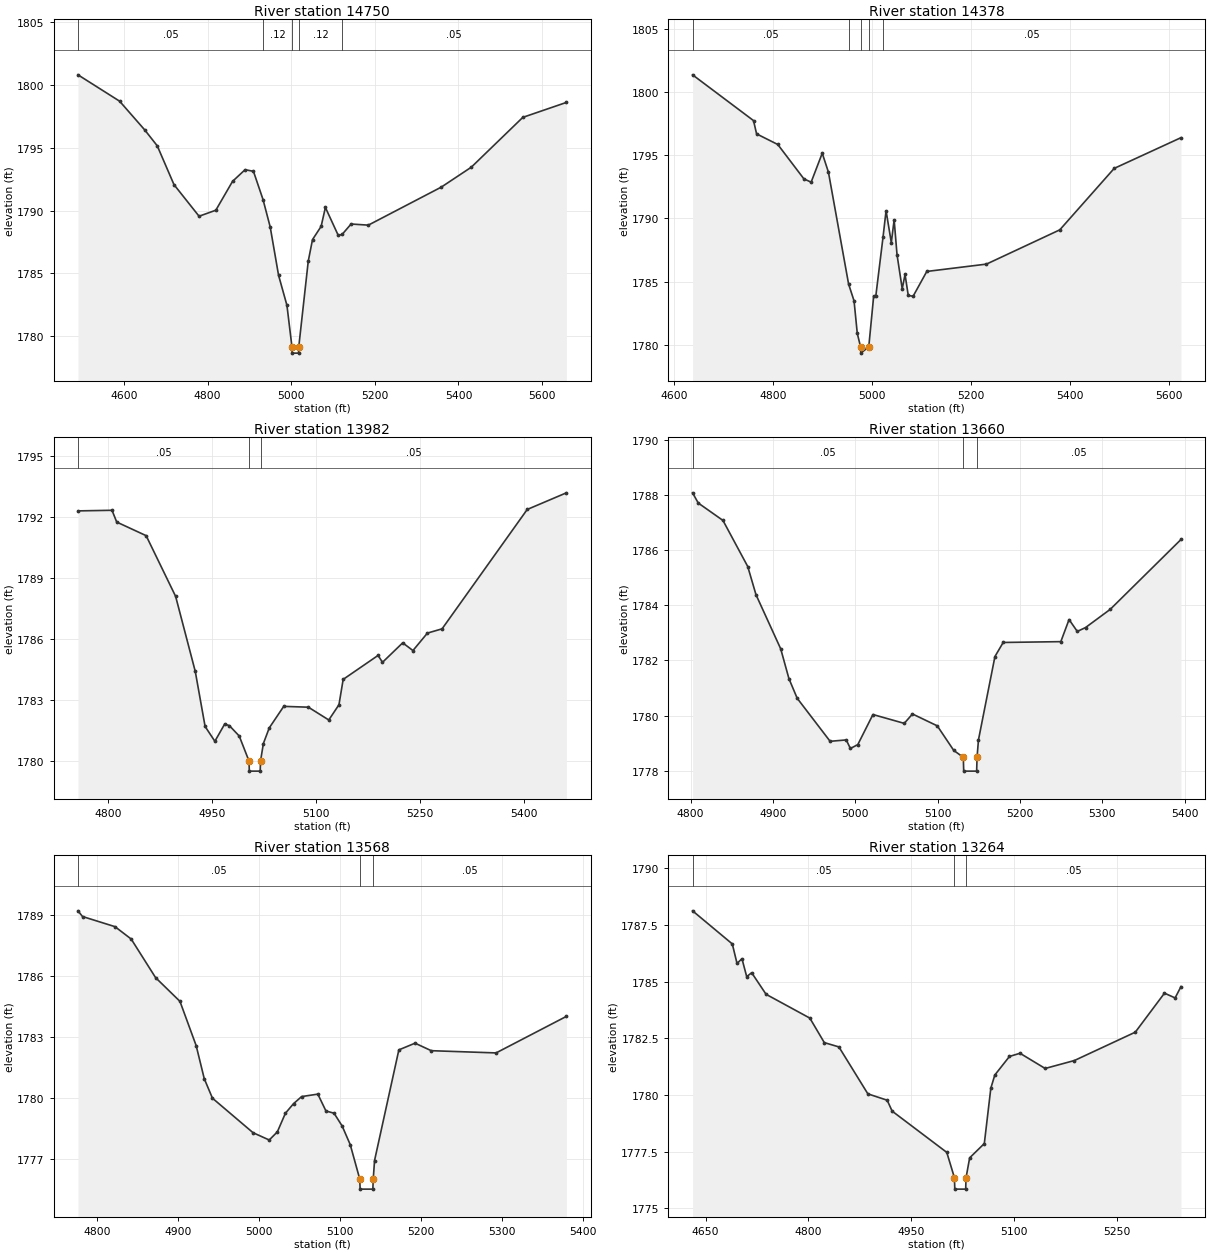
Type RM Length L Ch R = 1,14750,372,372,372
BEGIN DESCRIPTION:
Elm 02 18 14749.63
END DESCRIPTION:
XS GIS Cut Line= 3
      1619425.35      6838278.44      1619407.12      6838791.49
      1619555.55      6839429.47
#Sta/Elev= 30
  4489.8 1800.82  4589.4 1798.72  4649.5 1796.43  4679.5 1795.16  4719.5 1792.07
  4779.5 1789.55  4819.6 1790.03  4859.6 1792.33  4889.6 1793.26  4909.6 1793.13
  4932.5 1790.88  4949.7 1788.69  4969.7 1784.84  4989.7 1782.45  5001.7 1779.14
  5002.2 1778.64  5017.5 1778.64  5018.0 1779.14  5040.7 1785.97  5050.9 1787.69
  5071.5 1788.74  5081.7 1790.25  5112.5 1788.02  5121.7 1788.10  5143.2 1788.93
  5184.4 1788.84  5358.9 1791.87  5430.8 1793.46  5554.0 1797.43  5658.2 1798.62
#Mann=5,-1,0
  4489.8    0.05       0  4932.5    0.12       0  5001.7    0.07       0
  5018.0    0.12       0  5121.7    0.05       0
Bank Sta=5001.7,5018
Exp/Cntr=0.3,0.1

Type RM Length L Ch R = 1,14378,396,396,396
BEGIN DESCRIPTION:
Elm 02 18 14378.28
END DESCRIPTION:
XS GIS Cut Line= 3
      1618883.69      6838562.34      1619071.19      6838877.43
      1619362.50      6839423.64
#Sta/Elev= 30
  4638.0 1801.36  4761.0 1797.74  4767.2 1796.69  4810.0 1795.85  4862.7 1793.13
  4877.3 1792.87  4899.7 1795.16  4912.2 1793.66  4952.9 1784.81  4963.9 1783.48
  4970.4 1780.91  4977.0 1779.85  4977.5 1779.35  4993.6 1779.85  5003.5 1783.86
  5007.8 1783.86  5022.3 1788.50  5028.5 1790.61  5039.1 1788.09  5044.8 1789.89
  5050.6 1787.14  5061.1 1784.44  5066.8 1785.57  5073.3 1783.91  5083.1 1783.85
  5110.7 1785.81  5231.1 1786.39  5379.1 1789.10  5488.9 1793.96  5623.7 1796.39
#Mann=5,-1,0
  4638.0    0.05       0  4952.9    0.12       0  4977.0    0.07       0
  4993.6    0.12       0  5022.3    0.05       0
Bank Sta=4977,4993.6
Exp/Cntr=0.3,0.1

Type RM Length L Ch R = 1,13982,322,322,322
BEGIN DESCRIPTION:
Elm 02 18 13981.76
END DESCRIPTION:
XS GIS Cut Line= 3
      1618635.27      6838958.38      1618801.28      6839140.67
      1619068.56      6839514.00
#Sta/Elev= 30
  4756.1 1792.30  4805.3 1792.33  4812.1 1791.75  4854.6 1791.08  4897.2 1788.09
  4925.6 1784.39  4939.8 1781.68  4953.9 1780.95  4968.1 1781.80  4974.9 1781.72
  4989.1 1781.21  5003.2 1779.98  5003.7 1779.48  5019.4 1779.48  5019.9 1779.98
  5024.0 1780.84  5032.5 1781.61  5053.4 1782.67  5089.0 1782.63  5118.5 1782.00
  5133.2 1782.75  5139.3 1784.00  5189.7 1785.18  5196.1 1784.84  5225.3 1785.80
  5240.1 1785.42  5261.0 1786.28  5282.2 1786.49  5405.2 1792.37  5461.8 1793.19
#Mann=3,-1,0
  4756.1    0.05       0  5003.2    0.05       0  5019.9    0.05       0
Bank Sta=5003.2,5019.9
Exp/Cntr=0.3,0.1

Type RM Length L Ch R = 1,13660,92,92,92
BEGIN DESCRIPTION:
Elm 02 18 13660.04
END DESCRIPTION:
XS GIS Cut Line= 3
      1618566.21      6839141.07      1618559.70      6839341.60
      1618567.49      6839733.89
#Sta/Elev= 30
  4802.4 1788.07  4809.3 1787.70  4839.3 1787.07  4869.4 1785.40  4879.4 1784.38
  4909.4 1782.42  4919.4 1781.34  4929.4 1780.63  4969.4 1779.07  4989.0 1779.12
  4994.0 1778.81  5003.0 1778.95  5021.4 1780.04  5059.4 1779.72  5069.4 1780.06
  5099.5 1779.63  5119.5 1778.74  5131.1 1778.49  5131.6 1777.99  5147.3 1777.99
  5147.8 1778.49  5149.5 1779.12  5169.5 1782.14  5179.5 1782.65  5249.5 1782.68
  5259.5 1783.48  5269.5 1783.05  5279.5 1783.19  5309.5 1783.85  5395.4 1786.38
#Mann=3,-1,0
  4802.4    0.05       0  5131.1    0.05       0  5147.8    0.05       0
Bank Sta=5131.1,5147.8
Exp/Cntr=0.3,0.1

Type RM Length L Ch R = 1,13568,304,304,304
BEGIN DESCRIPTION:
Elm 02 18 13568.09
END DESCRIPTION:
XS GIS Cut Line= 3
      1618460.74      6839142.43      1618476.36      6839367.64
      1618475.07      6839744.79
#Sta/Elev= 30
  4776.5 1789.23  4782.1 1788.95  4822.2 1788.45  4842.2 1787.84  4872.3 1785.94
  4902.4 1784.77  4922.4 1782.59  4932.4 1780.96  4942.5 1780.00  4992.6 1778.30
  5012.6 1777.94  5022.6 1778.34  5032.6 1779.26  5042.6 1779.73  5052.6 1780.08
  5072.6 1780.20  5082.6 1779.37  5092.6 1779.26  5102.6 1778.63  5112.6 1777.71
  5124.3 1776.02  5124.8 1775.52  5140.5 1775.52  5141.0 1776.02  5142.6 1776.93
  5172.6 1782.38  5192.6 1782.71  5212.6 1782.34  5292.6 1782.23  5379.4 1784.03
#Mann=3,-1,0
  4776.5    0.05       0  5124.3    0.05       0  5141.0    0.05       0
Bank Sta=5124.3,5141
Exp/Cntr=0.3,0.1

Type RM Length L Ch R = 1,13264,366,366,366
BEGIN DESCRIPTION:
Elm 02 18 13263.87
END DESCRIPTION:
XS GIS Cut Line= 3
      1617988.10      6839283.03      1618244.59      6839551.24
      1618422.97      6839842.90
#Sta/Elev= 30
  4630.9 1788.12  4688.9 1786.66  4695.8 1785.80  4703.0 1786.01  4709.9 1785.22
  4717.2 1785.39  4738.2 1784.44  4802.1 1783.39  4823.2 1782.31  4844.5 1782.12
  4886.8 1780.05  4915.0 1779.77  4922.2 1779.29  5002.0 1777.47  5013.2 1776.35
  5013.7 1775.85  5029.6 1775.85  5030.1 1776.35  5035.4 1777.23  5056.8 1777.86
  5066.3 1780.30  5072.1 1780.88  5093.5 1781.70  5108.9 1781.84  5145.6 1781.17
  5188.3 1781.52  5277.2 1782.77  5319.8 1784.49  5335.3 1784.28  5343.9 1784.78
#Mann=3,-1,0
  4630.9    0.05       0  5013.2    0.05       0  5030.1    0.05       0
Bank Sta=5013.2,5030.1
Exp/Cntr=0.3,0.1

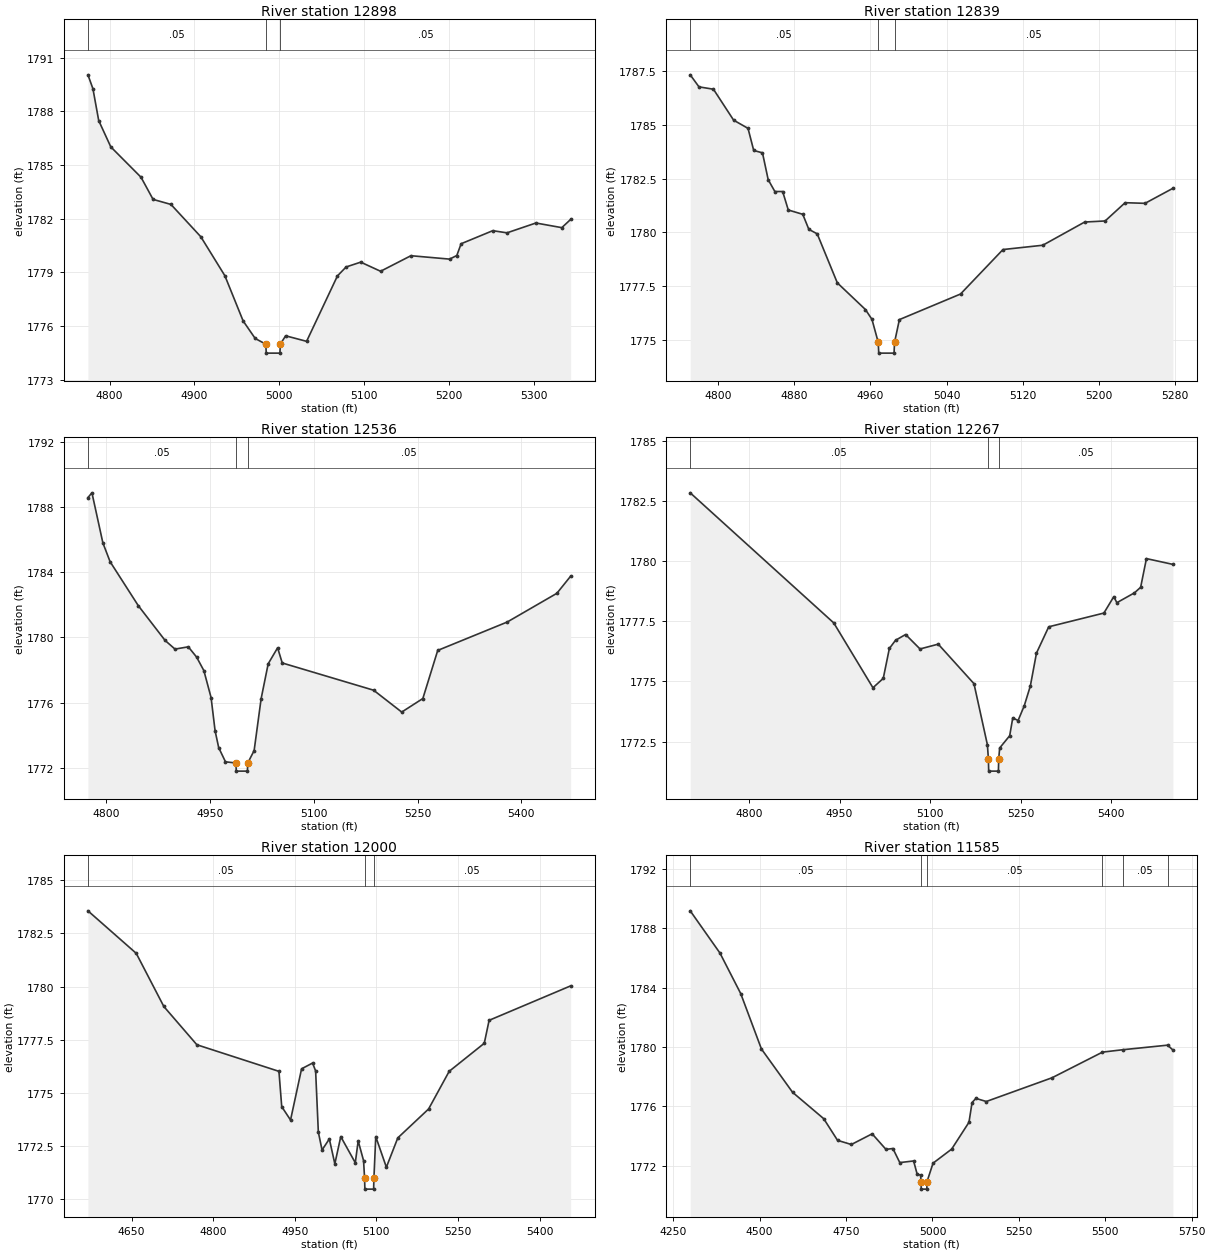
Type RM Length L Ch R = 1,12898,59,59,59
BEGIN DESCRIPTION:
Elm 02 18 12898.43
END DESCRIPTION:
XS GIS Cut Line= 4
      1617793.69      6839581.16      1617946.70      6839745.03
      1617979.26      6839751.54      1618285.29      6839805.80
#Sta/Elev= 30
  4774.6 1790.05  4780.5 1789.27  4787.3 1787.49  4801.5 1786.02  4837.1 1784.32
  4851.3 1783.08  4872.3 1782.80  4907.5 1780.99  4935.8 1778.81  4957.3 1776.28
  4971.5 1775.30  4984.0 1774.98  4984.5 1774.48  5000.6 1774.48  5001.1 1774.98
  5007.3 1775.45  5032.0 1775.14  5068.3 1778.80  5078.5 1779.30  5095.7 1779.57
  5119.1 1779.06  5154.8 1779.93  5200.3 1779.74  5208.8 1779.94  5213.9 1780.60
  5251.1 1781.33  5267.9 1781.21  5301.9 1781.76  5332.4 1781.50  5342.8 1781.96
#Mann=3,-1,0
  4774.6    0.05       0  4984.0    0.05       0  5001.1    0.05       0
Bank Sta=4984,5001.1
Exp/Cntr=0.3,0.1

Type RM Length L Ch R = 1,12839,303,303,303
BEGIN DESCRIPTION:
Elm 02 18 12839.29
END DESCRIPTION:
XS GIS Cut Line= 3
      1617710.19      6839659.33      1617904.39      6839784.09
      1618131.15      6839941.75
#Sta/Elev= 30
  4770.7 1787.33  4779.9 1786.77  4795.1 1786.66  4816.3 1785.22  4831.4 1784.84
  4837.4 1783.81  4846.6 1783.70  4852.6 1782.45  4859.6 1781.90  4867.8 1781.90
  4873.7 1781.04  4888.9 1780.84  4895.3 1780.14  4904.1 1779.93  4925.2 1777.65
  4954.7 1776.41  4961.6 1775.95  4968.2 1774.88  4968.7 1774.38  4984.8 1774.38
  4985.3 1774.88  4990.4 1775.94  5054.6 1777.13  5099.2 1779.20  5141.0 1779.40
  5185.0 1780.48  5206.5 1780.53  5227.5 1781.38  5248.4 1781.35  5277.7 1782.05
#Mann=3,-1,0
  4770.7    0.05       0  4968.2    0.05       0  4985.3    0.05       0
Bank Sta=4968.2,4985.3
Exp/Cntr=0.3,0.1

Type RM Length L Ch R = 1,12536,269,269,269
BEGIN DESCRIPTION:
Elm 02 18 12536.39
END DESCRIPTION:
XS GIS Cut Line= 3
      1617588.41      6839717.24      1617652.22      6839936.00
      1617734.24      6840398.21
#Sta/Elev= 30
  4773.9 1788.57  4779.7 1788.86  4795.5 1785.79  4805.9 1784.64  4846.7 1781.94
  4885.4 1779.81  4899.7 1779.28  4918.9 1779.42  4930.9 1778.79  4941.4 1777.96
  4951.8 1776.31  4957.6 1774.27  4962.8 1773.24  4972.6 1772.37  4987.7 1772.30
  4988.2 1771.80  5004.3 1771.80  5004.8 1772.30  5014.0 1773.06  5024.1 1776.24
  5034.3 1778.38  5047.9 1779.36  5054.6 1778.43  5186.6 1776.76  5227.2 1775.42
  5257.7 1776.25  5279.2 1779.20  5379.6 1780.94  5451.3 1782.70  5471.2 1783.75
#Mann=3,-1,0
  4773.9    0.05       0  4987.7    0.05       0  5004.8    0.05       0
Bank Sta=4987.7,5004.8
Exp/Cntr=0.3,0.1

Type RM Length L Ch R = 1,12267,267,267,267
BEGIN DESCRIPTION:
Elm 02 18 12267
END DESCRIPTION:
XS GIS Cut Line= 3
      1617329.30      6839706.82      1617399.61      6839997.20
      1617486.85      6840490.68
#Sta/Elev= 30
  4702.5 1782.83  4940.4 1777.43  5005.3 1774.74  5022.4 1775.13  5032.5 1776.37
  5042.7 1776.71  5059.4 1776.95  5083.3 1776.35  5113.5 1776.55  5172.7 1774.91
  5195.0 1772.37  5196.6 1771.78  5197.1 1771.28  5213.2 1771.28  5213.7 1771.78
  5215.3 1772.24  5231.9 1772.75  5237.0 1773.49  5245.8 1773.38  5256.0 1773.99
  5266.1 1774.81  5276.3 1776.18  5296.6 1777.27  5388.0 1777.84  5404.4 1778.52
  5409.5 1778.27  5438.7 1778.68  5448.9 1778.91  5458.5 1780.10  5502.4 1779.86
#Mann=3,-1,0
  4702.5    0.05       0  5196.6    0.05       0  5213.7    0.05       0
Bank Sta=5196.6,5213.7
Exp/Cntr=0.3,0.1

Type RM Length L Ch R = 1,12000,415,415,415
BEGIN DESCRIPTION:
Elm 02 18 12000.3
END DESCRIPTION:
XS GIS Cut Line= 3
      1617144.41      6839760.27      1617212.11      6840187.30
      1617348.83      6840620.89
#Sta/Elev= 30
  4569.9 1783.56  4658.7 1781.56  4709.4 1779.06  4770.1 1777.26  4920.9 1776.01
  4926.0 1774.35  4942.2 1773.72  4962.5 1776.13  4982.7 1776.40  4988.3 1776.03
  4993.3 1773.15  5000.1 1772.31  5013.5 1772.83  5023.6 1771.66  5034.5 1772.94
  5061.2 1771.71  5066.5 1772.74  5076.4 1771.81  5078.3 1770.97  5078.8 1770.47
  5094.9 1770.47  5095.4 1770.97  5098.8 1772.94  5118.3 1771.50  5139.3 1772.88
  5195.9 1774.24  5233.7 1776.01  5298.2 1777.33  5307.1 1778.41  5456.9 1780.03
#Mann=3,-1,0
  4569.9    0.05       0  5078.3    0.05       0  5095.4    0.05       0
Bank Sta=5078.3,5095.4
Exp/Cntr=0.3,0.1

Type RM Length L Ch R = 1,11585,156,156,156
BEGIN DESCRIPTION:
Elm 02 18 11584.98
END DESCRIPTION:
XS GIS Cut Line= 3
      1616980.60      6839732.00      1616954.56      6840435.13
      1616987.11      6841127.45
#Sta/Elev= 30
  4299.1 1789.19  4385.2 1786.34  4445.2 1783.61  4505.2 1779.87  4595.3 1776.95
  4685.4 1775.17  4725.4 1773.71  4765.4 1773.43  4825.5 1774.15  4865.5 1773.10
  4885.5 1773.16  4905.5 1772.21  4945.5 1772.32  4955.6 1771.44  4965.6 1771.36
  4967.0 1770.92  4967.5 1770.42  4983.7 1770.42  4984.2 1770.92  5001.7 1772.17
  5055.6 1773.12  5105.7 1774.93  5114.6 1776.26  5125.7 1776.54  5155.8 1776.33
  5346.0 1777.93  5492.0 1779.66  5550.1 1779.82  5680.4 1780.13  5695.8 1779.80
#Mann=6,-1,0
  4299.1    0.05       0  4967.0    0.03       0  4984.2    0.05       0
  5492.0   0.075       0  5550.1    0.05       0  5680.4   0.075       0
Bank Sta=4967,4984.2
Exp/Cntr=0.3,0.1

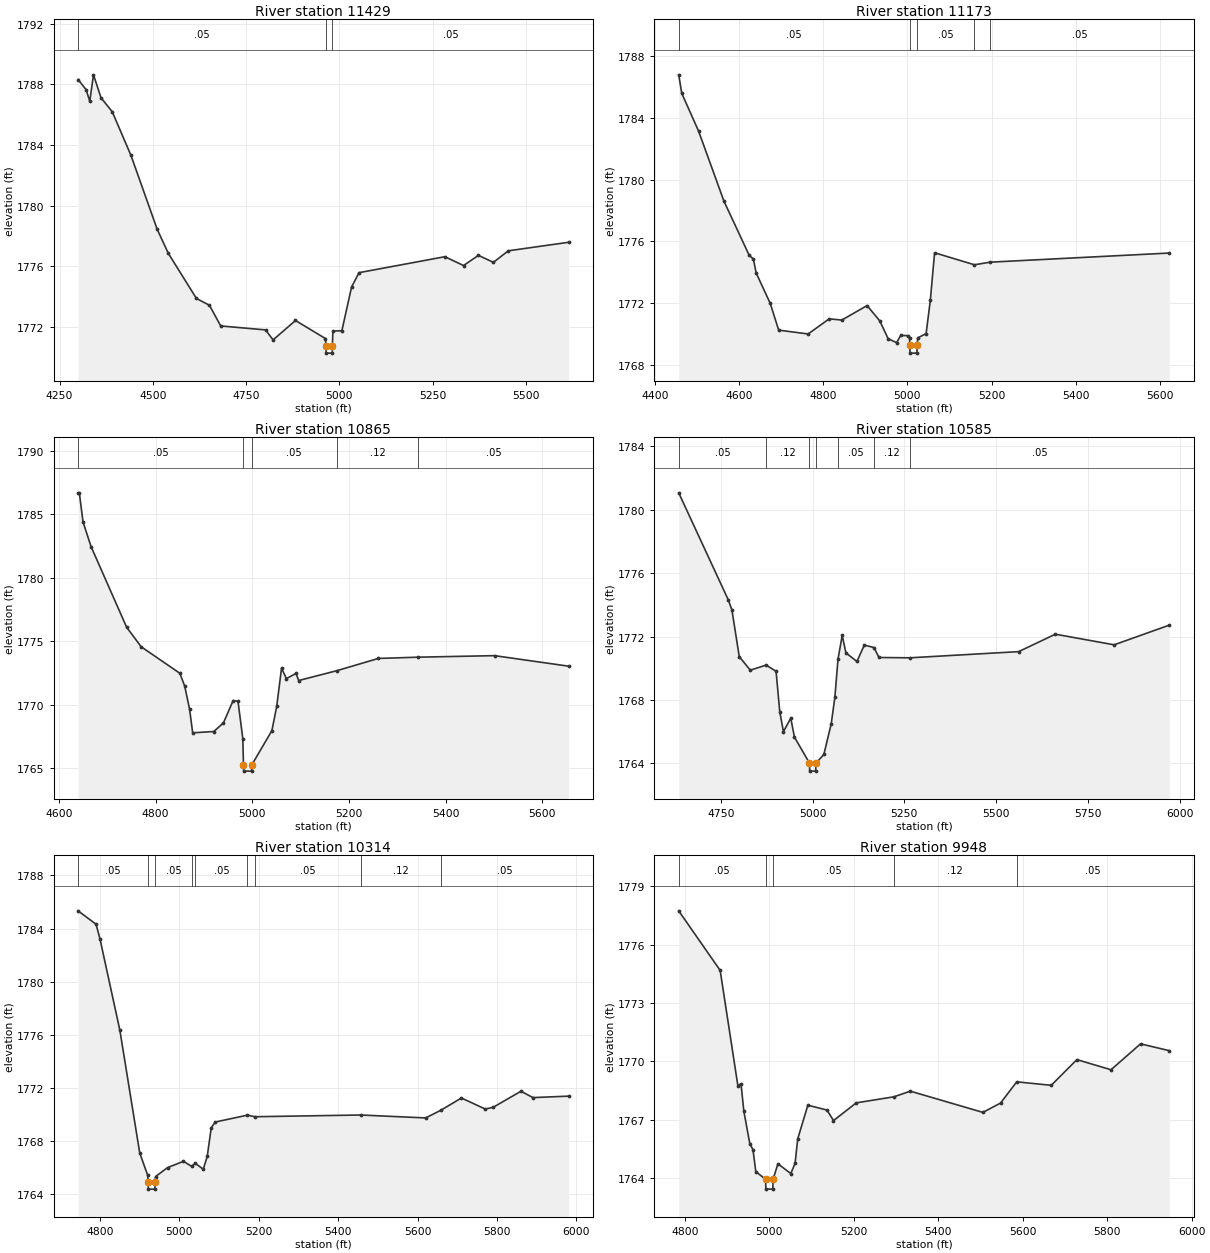
Type RM Length L Ch R = 1,11429,256,256,256
BEGIN DESCRIPTION:
Elm 02 18 11428.6
END DESCRIPTION:
XS GIS Cut Line= 3
      1616776.61      6839816.64      1616828.69      6840521.94
      1616811.33      6841129.57
#Sta/Elev= 30
  4299.7 1788.31  4321.1 1787.65  4331.1 1786.88  4341.0 1788.62  4361.2 1787.11
  4391.3 1786.19  4441.4 1783.32  4511.6 1778.46  4541.7 1776.86  4617.1 1773.89
  4652.0 1773.44  4682.1 1772.08  4802.4 1771.82  4822.5 1771.16  4882.6 1772.44
  4962.9 1771.25  4964.2 1770.79  4964.7 1770.29  4981.0 1770.29  4981.5 1770.79
  4982.9 1771.75  5006.9 1771.76  5033.0 1774.65  5053.0 1775.59  5283.1 1776.64
  5333.1 1776.06  5373.1 1776.73  5413.1 1776.27  5453.2 1777.03  5614.8 1777.59
#Mann=3,-1,0
  4299.7    0.05       0  4964.2    0.03       0  4981.5    0.05       0
Bank Sta=4964.2,4981.5
Exp/Cntr=0.3,0.1

Type RM Length L Ch R = 1,11173,308,308,308
BEGIN DESCRIPTION:
Elm 02 18 11173.25
END DESCRIPTION:
XS GIS Cut Line= 3
      1616584.87      6839940.73      1616600.06      6840489.81
      1616550.18      6841103.49
#Sta/Elev= 30
  4456.9 1786.79  4464.2 1785.59  4504.2 1783.14  4564.2 1778.62  4624.2 1775.11
  4634.2 1774.86  4640.9 1773.96  4674.3 1771.99  4694.3 1770.26  4764.3 1770.01
  4814.3 1770.99  4844.3 1770.91  4904.3 1771.85  4934.4 1770.86  4954.4 1769.70
  4974.4 1769.45  4984.4 1769.92  5001.7 1769.90  5005.1 1769.75  5005.8 1769.27
  5006.3 1768.77  5022.6 1768.77  5023.1 1769.27  5024.4 1769.75  5044.5 1770.04
  5054.5 1772.19  5064.6 1775.27  5159.2 1774.49  5196.4 1774.66  5621.9 1775.25
#Mann=5,-1,0
  4456.9    0.05       0  5005.8    0.05       0  5023.1    0.05       0
  5159.2    0.12       0  5196.4    0.05       0
Bank Sta=5005.8,5023.1
Exp/Cntr=0.3,0.1

Type RM Length L Ch R = 1,10865,280,280,280
BEGIN DESCRIPTION:
Elm 02 18 10864.72
END DESCRIPTION:
XS GIS Cut Line= 3
      1616361.34      6839977.69      1616343.98      6840342.24
      1616315.77      6840991.07
#Sta/Elev= 30
  4639.8 1786.69  4642.4 1786.69  4650.1 1784.39  4666.6 1782.46  4740.2 1776.10
  4770.3 1774.56  4850.3 1772.47  4860.4 1771.45  4870.4 1769.64  4876.8 1767.78
  4920.4 1767.88  4940.4 1768.56  4960.5 1770.32  4970.5 1770.27  4980.5 1767.32
  4981.9 1765.26  4982.4 1764.76  4998.7 1764.76  4999.2 1765.26  5040.6 1767.95
  5050.6 1769.86  5060.6 1772.88  5070.6 1772.05  5090.6 1772.46  5096.0 1771.90
  5174.5 1772.67  5260.8 1773.64  5343.8 1773.74  5501.0 1773.86  5654.2 1773.03
#Mann=5,-1,0
  4639.8    0.05       0  4981.9    0.05       0  4999.2    0.05       0
  5174.5    0.12       0  5343.8    0.05       0
Bank Sta=4981.9,4999.2
Exp/Cntr=0.3,0.1

Type RM Length L Ch R = 1,10585,271,271,271
BEGIN DESCRIPTION:
Elm 02 18 10584.81
END DESCRIPTION:
XS GIS Cut Line= 3
      1616083.57      6839973.31      1616064.03      6840342.24
      1616033.08      6841307.90
#Sta/Elev= 30
  4635.6 1781.07  4770.5 1774.32  4780.5 1773.68  4800.5 1770.73  4830.6 1769.88
  4873.5 1770.20  4900.7 1769.81  4910.7 1767.27  4920.7 1766.00  4940.7 1766.85
  4950.7 1765.66  4991.7 1764.01  4992.2 1763.51  5008.6 1763.51  5009.1 1764.01
  5030.8 1764.56  5050.8 1766.49  5060.8 1768.16  5069.3 1770.57  5080.8 1772.07
  5090.9 1770.97  5120.9 1770.43  5140.9 1771.46  5167.2 1771.31  5180.9 1770.68
  5265.1 1770.66  5561.1 1771.05  5661.1 1772.15  5821.2 1771.48  5971.2 1772.72
#Mann=7,-1,0
  4635.6    0.05       0  4873.5    0.12       0  4991.7    0.07       0
  5009.1    0.12       0  5069.3    0.05       0  5167.2    0.12       0
  5265.1    0.05       0
Bank Sta=4991.7,5009.1
Exp/Cntr=0.3,0.1

Type RM Length L Ch R = 1,10314,366,366,366
BEGIN DESCRIPTION:
Elm 02 18 10313.85
END DESCRIPTION:
XS GIS Cut Line= 3
      1615797.97      6840072.71      1615795.37      6840331.82
      1615793.50      6841307.89
#Sta/Elev= 30
  4745.1 1785.34  4790.4 1784.33  4800.4 1783.21  4850.4 1776.34  4900.4 1767.11
  4920.4 1765.43  4921.7 1764.89  4922.2 1764.39  4938.6 1764.39  4939.1 1764.89
  4940.4 1765.34  4970.4 1766.01  5010.4 1766.48  5030.9 1766.11  5040.2 1766.33
  5060.4 1765.89  5070.4 1766.86  5080.4 1769.00  5090.4 1769.44  5171.7 1769.96
  5190.0 1769.84  5456.6 1769.97  5620.4 1769.75  5658.2 1770.32  5710.4 1771.25
  5770.4 1770.42  5790.4 1770.55  5860.4 1771.76  5890.4 1771.28  5980.3 1771.39
#Mann=9,-1,0
  4745.1    0.05       0  4921.7    0.05       0  4939.1    0.05       0
  5030.9    0.12       0  5040.2    0.05       0  5171.7    0.12       0
  5190.0    0.05       0  5456.6    0.12       0  5658.2    0.05       0
Bank Sta=4921.7,4939.1
Exp/Cntr=0.3,0.1

Type RM Length L Ch R = 1,9948,182,182,182
BEGIN DESCRIPTION:
Elm 02 18 9901.414
END DESCRIPTION:
XS GIS Cut Line= 3
      1615638.21      6840142.90      1615479.91      6840287.79
      1615619.37      6841224.36
#Sta/Elev= 30
  4785.4 1777.73  4883.6 1774.67  4925.5 1768.75  4932.9 1768.85  4939.7 1767.43
  4953.8 1765.77  4961.2 1765.47  4968.0 1764.34  4991.2 1763.94  4991.7 1763.44
  5008.2 1763.44  5008.7 1763.94  5020.4 1764.74  5050.8 1764.24  5060.9 1764.76
  5067.2 1766.02  5091.2 1767.75  5136.5 1767.50  5151.9 1766.96  5205.9 1767.87
  5294.9 1768.18  5333.9 1768.47  5505.7 1767.38  5547.5 1767.86  5585.8 1768.95
  5667.5 1768.77  5728.2 1770.09  5809.0 1769.57  5879.0 1770.90  5946.9 1770.55
#Mann=5,-1,0
  4785.4    0.05       0  4991.2    0.05       0  5008.7    0.05       0
  5294.9    0.12       0  5585.8    0.05       0
Bank Sta=4991.2,5008.7
Exp/Cntr=0.3,0.1