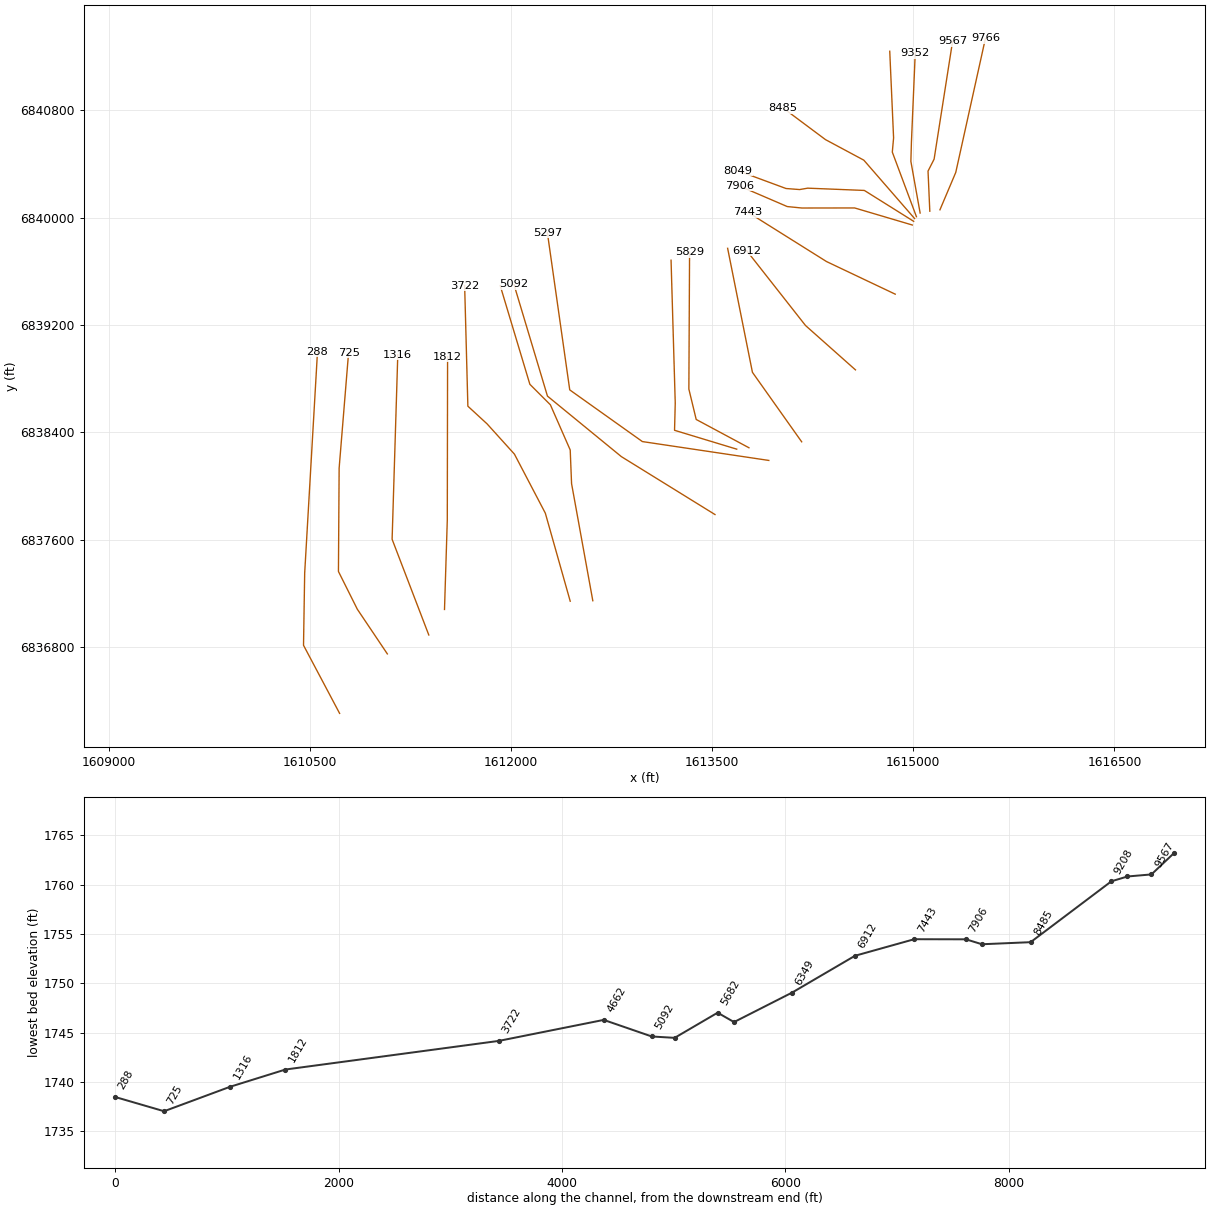
HEC-RAS study Elm 02 18.prj: Elm 02 18 Base Level Engineering

--- Elm 02 18.g01 (geometry) --- (continued)

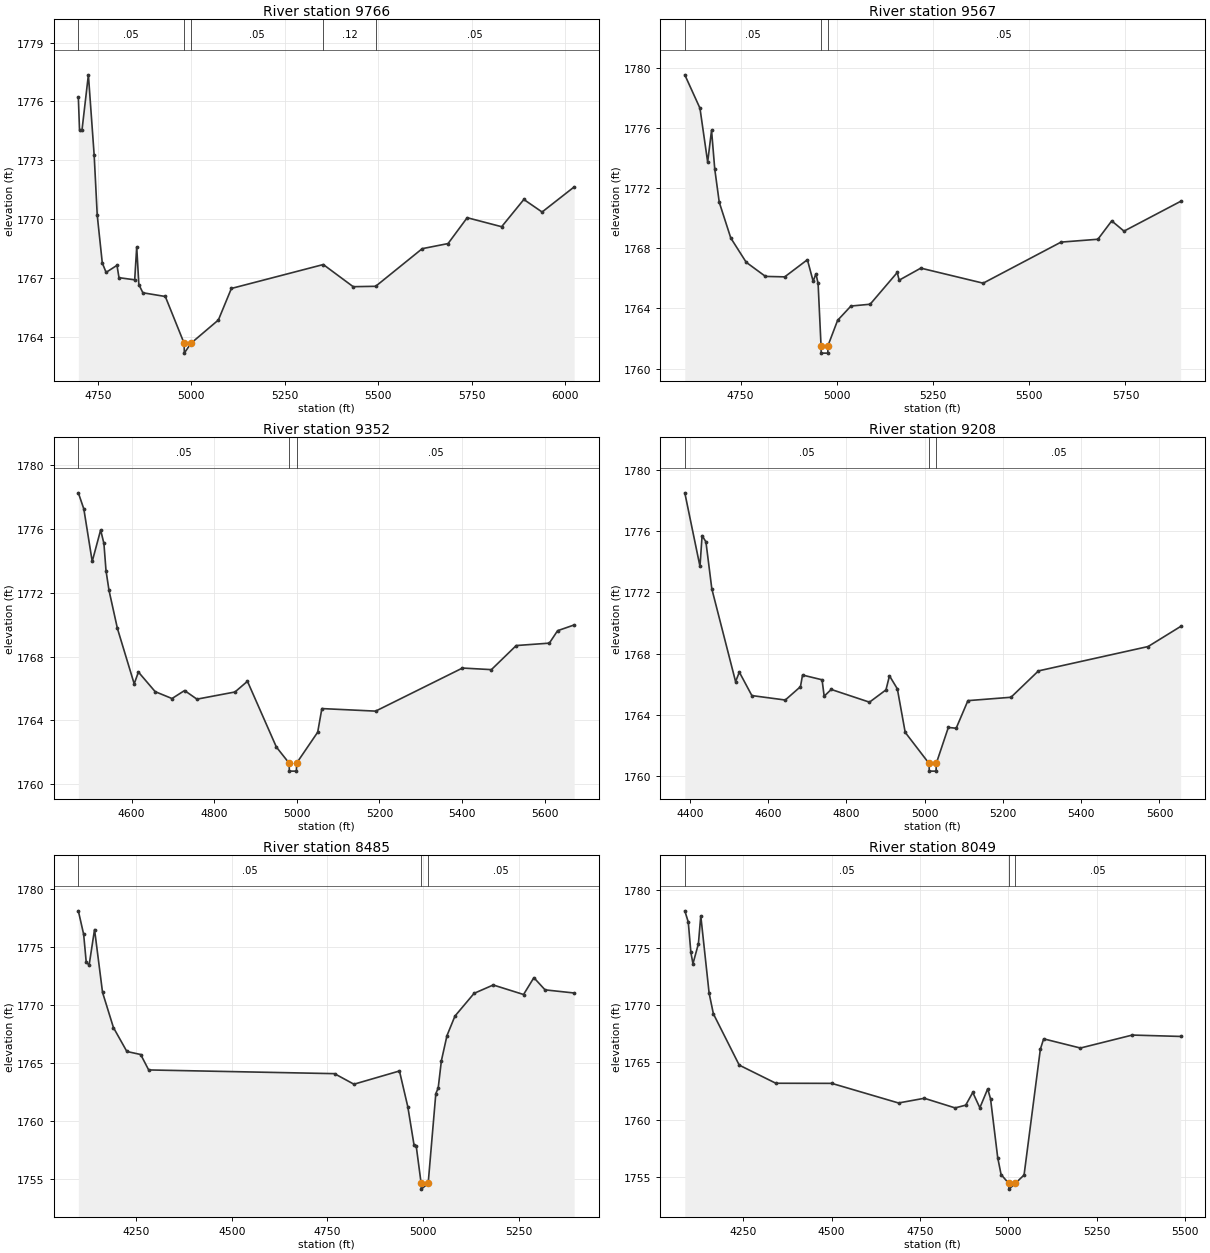
Type RM Length L Ch R = 1,9766,199,199,199
BEGIN DESCRIPTION:
Elm 02 18 9423.376
END DESCRIPTION:
XS GIS Cut Line= 3
      1615199.22      6840058.93      1615317.10      6840337.62
      1615538.41      6841337.42
#Sta/Elev= 30
  4697.4 1776.22  4700.6 1774.55  4707.2 1774.54  4724.3 1777.36  4739.8 1773.25
  4748.0 1770.19  4761.5 1767.76  4771.7 1767.28  4800.8 1767.64  4806.2 1767.01
  4848.2 1766.90  4853.6 1768.58  4859.3 1766.66  4870.1 1766.24  4930.1 1766.05
  4980.5 1763.66  4981.0 1763.16  4998.6 1763.66  5072.1 1764.85  5106.9 1766.46
  5352.8 1767.68  5432.8 1766.55  5492.9 1766.57  5617.5 1768.49  5686.6 1768.75
  5737.8 1770.07  5830.0 1769.61  5889.4 1771.00  5938.2 1770.36  6024.0 1771.64
#Mann=5,-1,0
  4697.4    0.05       0  4980.5    0.05       0  4998.6    0.05       0
  5352.8    0.12       0  5492.9    0.05       0
Bank Sta=4980.5,4998.6
Exp/Cntr=0.3,0.1

Type RM Length L Ch R = 1,9567,215,215,215
BEGIN DESCRIPTION:
Elm 02 18 9567.21
END DESCRIPTION:
XS GIS Cut Line= 4
      1615123.59      6840048.61      1615110.35      6840347.43
      1615155.61      6840436.41      1615293.35      6841314.84
#Sta/Elev= 30
  4605.2 1779.53  4644.6 1777.31  4664.6 1773.73  4674.7 1775.84  4683.0 1773.27
  4694.7 1771.06  4724.7 1768.68  4764.7 1767.07  4814.8 1766.13  4864.8 1766.10
  4923.7 1767.24  4938.6 1765.81  4945.9 1766.30  4951.5 1765.66  4959.1 1761.53
  4959.6 1761.03  4976.7 1761.03  4977.2 1761.53  5002.2 1763.21  5036.8 1764.16
  5086.7 1764.28  5157.1 1766.39  5162.1 1765.88  5218.3 1766.68  5380.3 1765.68
  5582.7 1768.41  5678.4 1768.60  5714.3 1769.82  5746.2 1769.14  5893.3 1771.12
#Mann=3,-1,0
  4605.2    0.05       0  4959.1    0.05       0  4977.2    0.05       0
Bank Sta=4959.1,4977.2
Exp/Cntr=0.3,0.1

Type RM Length L Ch R = 1,9352,144,144,144
BEGIN DESCRIPTION:
Elm 02 18 9351.91
END DESCRIPTION:
XS GIS Cut Line= 4
      1615051.41      6840034.88      1614982.45      6840420.07
      1614986.34      6840558.81      1615014.98      6841228.09
#Sta/Elev= 30
  4471.3 1778.26  4484.6 1777.25  4504.9 1773.96  4525.3 1775.93  4533.2 1775.09
  4538.3 1773.38  4545.6 1772.14  4565.9 1769.76  4606.5 1766.29  4616.7 1767.03
  4657.3 1765.80  4698.0 1765.37  4728.4 1765.87  4758.4 1765.33  4850.4 1765.78
  4880.6 1766.45  4950.6 1762.33  4981.5 1761.32  4982.0 1760.82  4999.1 1760.82
  4999.6 1761.32  5050.6 1763.26  5060.7 1764.74  5190.8 1764.58  5401.0 1767.28
  5471.0 1767.18  5531.1 1768.69  5611.2 1768.84  5631.2 1769.62  5671.3 1769.98
#Mann=3,-1,0
  4471.3    0.05       0  4981.5    0.05       0  4999.6    0.05       0
Bank Sta=4981.5,4999.6
Exp/Cntr=0.3,0.1

Type RM Length L Ch R = 1,9208,723,723,723
BEGIN DESCRIPTION:
Elm 02 18 9208.35
END DESCRIPTION:
XS GIS Cut Line= 4
      1615023.89      6840007.42      1614844.02      6840489.03
      1614853.52      6840595.26      1614824.88      6841241.07
#Sta/Elev= 30
  4386.8 1778.49  4425.6 1773.69  4431.0 1775.70  4440.8 1775.29  4455.9 1772.22
  4516.6 1766.17  4526.2 1766.79  4558.2 1765.26  4643.6 1764.97  4682.4 1765.84
  4687.7 1766.60  4737.6 1766.29  4743.0 1765.22  4761.0 1765.66  4858.8 1764.83
  4900.9 1765.63  4909.9 1766.55  4930.0 1765.70  4950.1 1762.86  5011.1 1760.83
  5011.6 1760.33  5029.0 1760.33  5029.5 1760.83  5060.3 1763.18  5080.4 1763.13
  5110.4 1764.93  5220.5 1765.15  5290.6 1766.87  5570.9 1768.46  5654.0 1769.77
#Mann=3,-1,0
  4386.8    0.05       0  5011.1    0.05       0  5029.5    0.05       0
Bank Sta=5011.1,5029.5
Exp/Cntr=0.3,0.1

Type RM Length L Ch R = 1,8485,436,436,436
BEGIN DESCRIPTION:
Elm 02 18 8485.22
END DESCRIPTION:
XS GIS Cut Line= 4
      1615010.15      6839993.63      1614631.64      6840428.99
      1614345.71      6840582.24      1614029.01      6840818.47
#Sta/Elev= 30
  4098.9 1778.14  4112.8 1776.12  4119.5 1773.73  4127.1 1773.46  4141.3 1776.53
  4162.2 1771.11  4190.7 1768.08  4225.8 1766.02  4261.9 1765.76  4282.8 1764.43
  4768.7 1764.11  4819.5 1763.20  4938.5 1764.34  4960.4 1761.25  4976.6 1757.97
  4982.3 1757.88  4995.2 1754.66  4995.7 1754.16  5013.6 1754.66  5033.6 1762.39
  5039.8 1762.87  5048.2 1765.23  5062.8 1767.39  5083.6 1769.07  5133.7 1771.03
  5183.7 1771.75  5263.0 1770.93  5290.0 1772.38  5319.2 1771.33  5395.3 1771.06
#Mann=3,-1,0
  4098.9    0.05       0  4995.2    0.03       0  5013.6    0.05       0
Bank Sta=4995.2,5013.6
Exp/Cntr=0.3,0.1

Type RM Length L Ch R = 1,8049,143,143,143
BEGIN DESCRIPTION:
Elm 02 18 8048.64
END DESCRIPTION:
XS GIS Cut Line= 6
      1615003.27      6839973.01      1614635.47      6840203.31
      1614212.90      6840220.26      1614153.00      6840209.85
      1614051.44      6840217.66      1613692.02      6840350.49
#Sta/Elev= 30
  4084.8 1778.21  4094.6 1777.24  4102.0 1774.58  4107.9 1773.60  4123.3 1775.34
  4130.0 1777.78  4153.6 1771.03  4165.7 1769.23  4238.8 1764.76  4342.3 1763.18
  4500.5 1763.17  4689.4 1761.46  4762.4 1761.87  4849.5 1761.03  4879.5 1761.27
  4899.5 1762.38  4919.5 1761.04  4941.7 1762.69  4949.7 1761.83  4970.0 1756.70
  4979.6 1755.22  5001.3 1754.45  5001.8 1753.95  5019.7 1754.45  5044.6 1755.18
  5090.7 1766.15  5100.0 1767.05  5204.0 1766.25  5350.8 1767.38  5487.5 1767.26
#Mann=3,-1,0
  4084.8    0.05       0  5001.3    0.05       0  5019.7    0.05       0
Bank Sta=5001.3,5019.7
Exp/Cntr=0.3,0.1

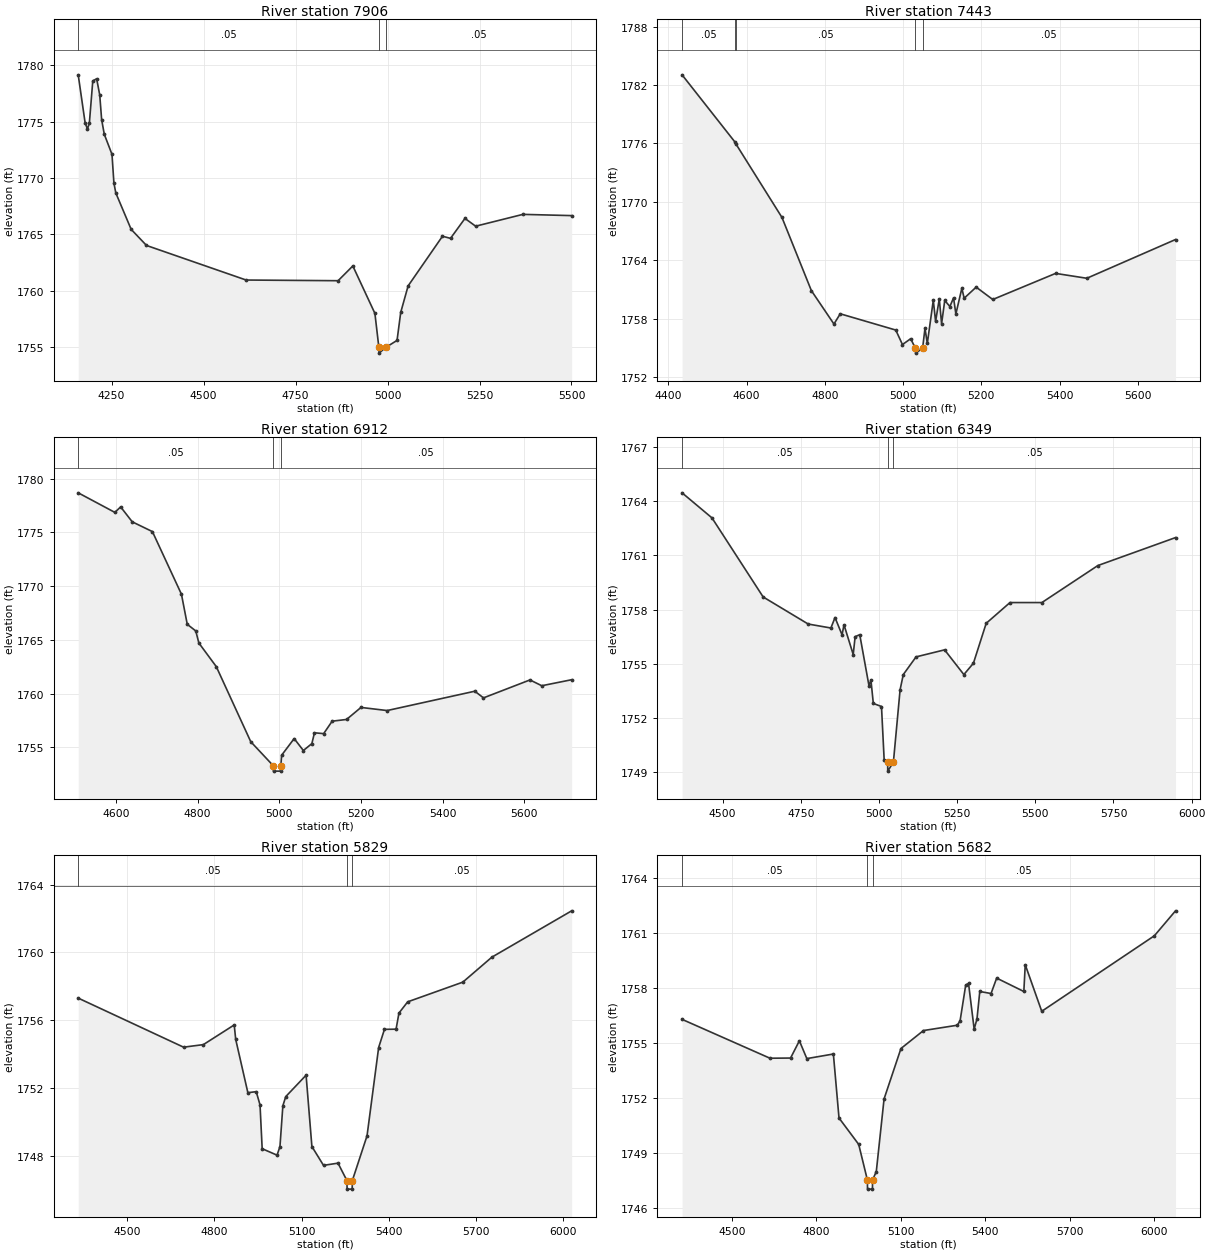
Type RM Length L Ch R = 1,7906,463,463,463
BEGIN DESCRIPTION:
Elm 02 18 7906.81
END DESCRIPTION:
XS GIS Cut Line= 5
      1614993.01      6839945.49      1614563.28      6840072.69
      1614169.06      6840072.26      1614060.55      6840083.11
      1613702.52      6840237.17
#Sta/Elev= 30
  4159.3 1779.16  4178.1 1774.89  4184.5 1774.34  4189.7 1774.91  4198.9 1778.62
  4209.4 1778.81  4217.8 1777.37  4223.0 1775.17  4230.2 1773.88  4251.1 1772.10
  4256.3 1769.56  4261.5 1768.67  4303.2 1765.44  4344.9 1764.01  4615.7 1760.94
  4865.7 1760.88  4905.7 1762.19  4965.7 1757.98  4976.5 1754.95  4977.0 1754.45
  4994.9 1754.95  5025.9 1755.58  5035.9 1758.07  5056.0 1760.42  5149.4 1764.83
  5171.2 1764.64  5210.5 1766.41  5239.5 1765.72  5368.0 1766.77  5500.5 1766.66
#Mann=3,-1,0
  4159.3    0.05       0  4976.5    0.05       0  4994.9    0.05       0
Bank Sta=4976.5,4994.9
Exp/Cntr=0.3,0.1

Type RM Length L Ch R = 1,7443,531,531,531
BEGIN DESCRIPTION:
Elm 02 18 7443.29
END DESCRIPTION:
XS GIS Cut Line= 3
      1614865.69      6839429.90      1614353.52      6839672.96
      1613765.38      6840041.90
#Sta/Elev= 30
  4435.2 1783.05  4570.1 1776.16  4572.2 1775.99  4690.5 1768.40  4765.7 1760.88
  4823.4 1757.45  4839.5 1758.50  4981.4 1756.83  4998.5 1755.34  5019.5 1755.94
  5031.6 1754.96  5032.1 1754.46  5050.0 1754.96  5056.1 1757.02  5062.0 1755.45
  5077.3 1759.89  5083.2 1757.72  5092.6 1760.03  5098.5 1757.48  5106.6 1759.87
  5119.7 1759.25  5129.1 1760.14  5135.0 1758.48  5150.3 1761.12  5156.2 1760.10
  5186.9 1761.24  5229.3 1759.97  5389.9 1762.65  5469.7 1762.15  5696.4 1766.13
#Mann=5,-1,0
  4435.2    0.05       0  4570.1    0.12       0  4572.2    0.05       0
  5031.6    0.05       0  5050.0    0.05       0
Bank Sta=5031.6,5050
Exp/Cntr=0.3,0.1

Type RM Length L Ch R = 1,6912,563,563,563
BEGIN DESCRIPTION:
Elm 02 18 6911.6
END DESCRIPTION:
XS GIS Cut Line= 3
      1614569.23      6838865.38      1614196.84      6839196.10
      1613757.92      6839754.49
#Sta/Elev= 30
  4507.9 1778.69  4597.6 1776.87  4611.8 1777.38  4640.2 1775.99  4689.6 1775.08
  4760.7 1769.25  4774.9 1766.45  4795.8 1765.83  4803.3 1764.71  4846.0 1762.51
  4930.4 1755.52  4985.6 1753.28  4986.1 1752.78  5003.6 1752.78  5004.1 1753.28
  5006.0 1754.26  5036.7 1755.81  5059.2 1754.70  5080.0 1755.34  5086.4 1756.35
  5108.9 1756.27  5129.7 1757.43  5165.0 1757.59  5200.3 1758.71  5264.4 1758.42
  5479.0 1760.22  5500.3 1759.60  5614.1 1761.27  5643.0 1760.73  5716.2 1761.29
#Mann=3,-1,0
  4507.9    0.05       0  4985.6    0.05       0  5004.1    0.05       0
Bank Sta=4985.6,5004.1
Exp/Cntr=0.3,0.1

Type RM Length L Ch R = 1,6349,520,520,520
BEGIN DESCRIPTION:
Elm 02 18 6349.39
END DESCRIPTION:
XS GIS Cut Line= 3
      1614168.18      6838328.93      1613801.01      6838847.15
      1613616.11      6839771.62
#Sta/Elev= 30
  4370.5 1764.47  4466.2 1763.08  4629.8 1758.70  4773.8 1757.20  4846.4 1756.98
  4859.6 1757.56  4882.1 1756.60  4888.3 1757.16  4917.8 1755.51  4923.9 1756.50
  4938.7 1756.61  4968.3 1753.77  4974.4 1754.10  4982.1 1752.80  5008.2 1752.63
  5016.7 1749.69  5027.8 1749.55  5028.3 1749.05  5046.3 1749.55  5067.7 1753.56
  5077.9 1754.40  5118.7 1755.38  5210.0 1755.77  5271.6 1754.40  5302.2 1755.03
  5343.0 1757.24  5419.1 1758.39  5521.1 1758.39  5700.0 1760.44  5948.4 1761.99
#Mann=3,-1,0
  4370.5    0.05       0  5027.8    0.05       0  5046.3    0.05       0
Bank Sta=5027.8,5046.3
Exp/Cntr=0.3,0.1

Type RM Length L Ch R = 1,5829,147,147,147
BEGIN DESCRIPTION:
Elm 02 18 5829.46
END DESCRIPTION:
XS GIS Cut Line= 4
      1613774.93      6838284.67      1613381.74      6838495.58
      1613327.05      6838722.15      1613332.26      6839742.97
#Sta/Elev= 30
  4330.5 1757.31  4693.5 1754.42  4761.6 1754.57  4868.0 1755.73  4873.1 1754.88
  4915.0 1751.74  4943.8 1751.80  4956.9 1751.02  4964.3 1748.44  5015.6 1748.06
  5025.6 1748.57  5035.6 1750.97  5045.6 1751.51  5115.6 1752.77  5135.6 1748.57
  5175.6 1747.46  5225.6 1747.59  5256.4 1746.56  5256.9 1746.06  5274.4 1746.06
  5274.9 1746.56  5325.6 1749.20  5365.6 1754.40  5385.6 1755.47  5425.6 1755.48
  5435.6 1756.43  5465.6 1757.09  5655.6 1758.25  5755.6 1759.72  6030.6 1762.45
#Mann=3,-1,0
  4330.5    0.05       0  5256.4    0.05       0  5274.9    0.05       0
Bank Sta=5256.4,5274.9
Exp/Cntr=0.3,0.1

Type RM Length L Ch R = 1,5682,385,385,385
BEGIN DESCRIPTION:
Elm 02 18 5681.73
END DESCRIPTION:
XS GIS Cut Line= 4
      1613683.86      6838274.22      1613220.28      6838414.85
      1613225.49      6838617.98      1613194.23      6839683.09
#Sta/Elev= 30
  4322.5 1756.27  4634.8 1754.15  4708.0 1754.16  4739.3 1755.10  4765.8 1754.13
  4860.1 1754.38  4880.1 1750.89  4950.1 1749.45  4980.9 1747.51  4981.4 1747.01
  4998.9 1747.01  4999.4 1747.51  5012.6 1747.97  5040.2 1751.93  5100.2 1754.68
  5180.2 1755.66  5300.3 1755.95  5310.3 1756.19  5330.3 1758.14  5340.3 1758.23
  5360.3 1755.74  5370.3 1756.29  5380.3 1757.79  5420.3 1757.68  5440.3 1758.52
  5536.8 1757.79  5541.8 1759.25  5600.4 1756.71  6000.6 1760.83  6075.7 1762.19
#Mann=3,-1,0
  4322.5    0.05       0  4980.9    0.05       0  4999.4    0.05       0
Bank Sta=4980.9,4999.4
Exp/Cntr=0.3,0.1

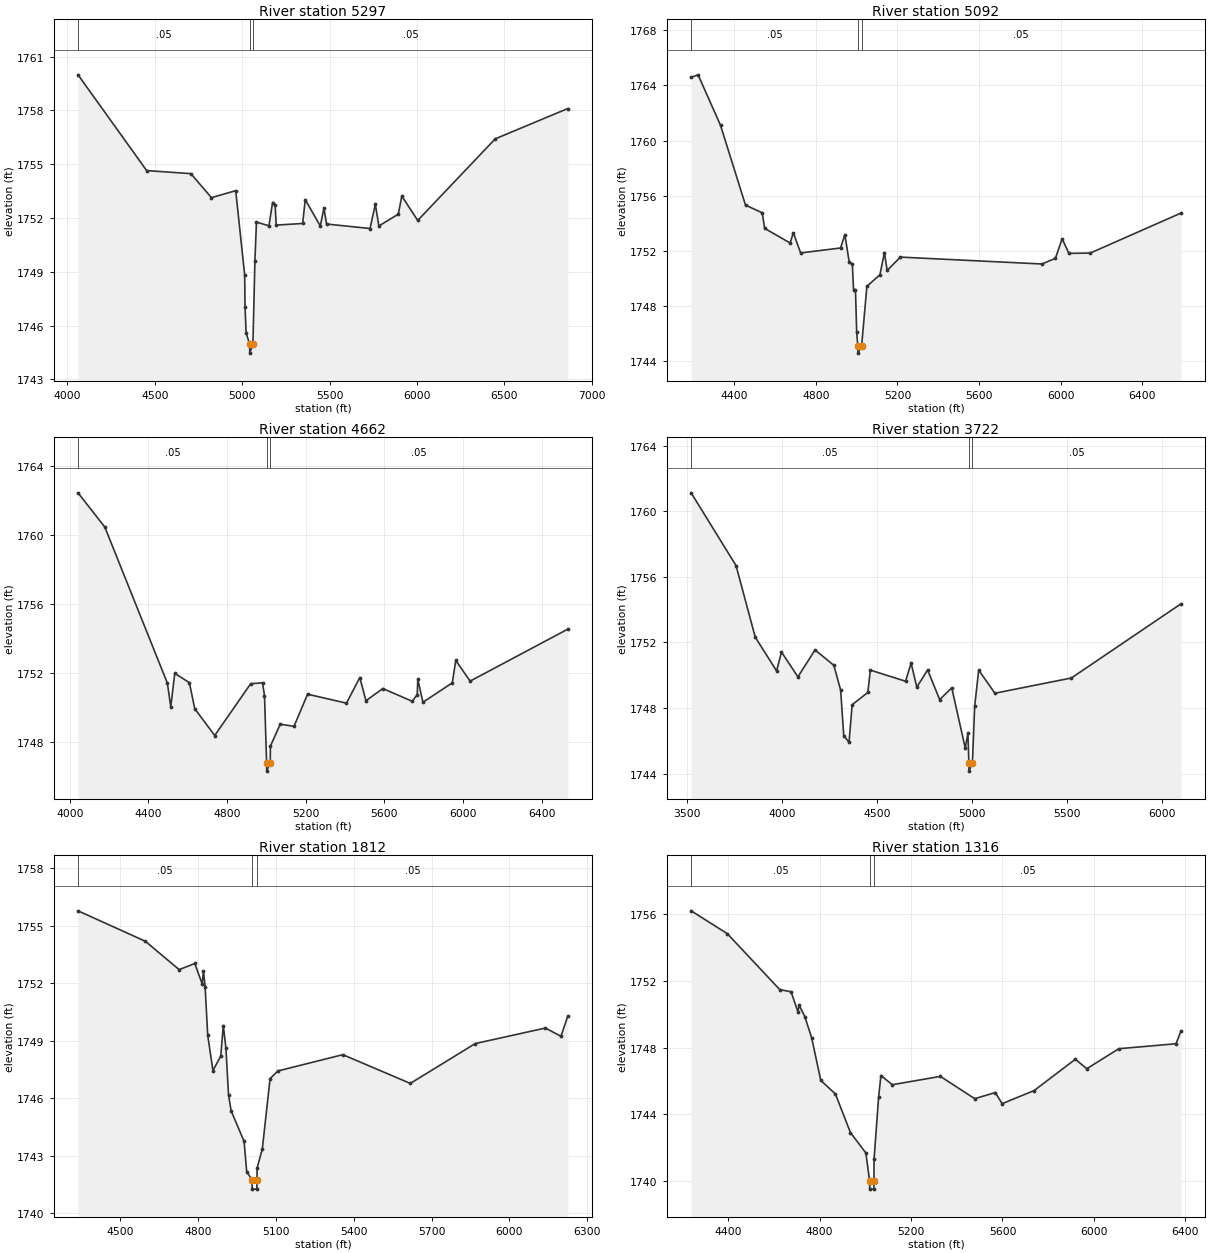
Type RM Length L Ch R = 1,5297,205,205,205
BEGIN DESCRIPTION:
Elm 02 18 5297.1
END DESCRIPTION:
XS GIS Cut Line= 4
      1613923.17      6838190.11      1612980.43      6838330.74
      1612438.77      6838716.16      1612272.10      6839888.01
#Sta/Elev= 30
  4060.9 1759.98  4453.4 1754.64  4706.1 1754.47  4824.2 1753.13  4962.8 1753.52
  5014.1 1748.82  5016.3 1747.04  5022.4 1745.58  5042.7 1744.96  5043.2 1744.46
  5061.2 1744.96  5072.8 1749.62  5081.5 1751.77  5152.8 1751.56  5173.7 1752.86
  5188.4 1752.71  5194.6 1751.60  5345.8 1751.69  5360.6 1753.02  5446.7 1751.55
  5467.6 1752.55  5482.3 1751.66  5731.2 1751.41  5761.5 1752.76  5781.7 1751.55
  5892.8 1752.21  5913.0 1753.22  6003.9 1751.86  6447.3 1756.41  6862.5 1758.10
#Mann=3,-1,0
  4060.9    0.05       0  5042.7    0.05       0  5061.2    0.05       0
Bank Sta=5042.7,5061.2
Exp/Cntr=0.3,0.1

Type RM Length L Ch R = 1,5092,430,430,430
BEGIN DESCRIPTION:
Elm 02 18 5092.41
END DESCRIPTION:
XS GIS Cut Line= 4
      1613521.71      6837786.76      1612823.85      6838218.41
      1612272.64      6838669.79      1612022.98      6839502.04
#Sta/Elev= 30
  4188.5 1764.59  4222.6 1764.77  4332.5 1761.11  4455.1 1755.33  4537.0 1754.77
  4549.1 1753.64  4674.1 1752.58  4689.5 1753.33  4725.5 1751.86  4921.1 1752.22
  4942.4 1753.19  4963.7 1751.19  4979.0 1751.08  4984.9 1749.21  4994.4 1749.15
  5000.3 1746.15  5005.9 1745.10  5006.4 1744.60  5024.4 1745.10  5050.3 1749.44
  5114.2 1750.28  5136.5 1751.89  5149.8 1750.59  5214.4 1751.56  5908.7 1751.06
  5974.9 1751.47  6007.9 1752.89  6041.0 1751.83  6145.4 1751.85  6590.4 1754.75
#Mann=3,-1,0
  4188.5    0.05       0  5005.9    0.05       0  5024.4    0.05       0
Bank Sta=5005.9,5024.4
Exp/Cntr=0.3,0.1

Type RM Length L Ch R = 1,4662,940,940,940
BEGIN DESCRIPTION:
Elm 02 18 4662.14
END DESCRIPTION:
XS GIS Cut Line= 6
      1612610.79      6837143.91      1612452.44      6838017.04
      1612442.34      6838268.00      1612294.53      6838604.87
      1612141.51      6838757.79      1611920.26      6839493.81
#Sta/Elev= 30
  4041.9 1762.45  4178.2 1760.46  4496.5 1751.39  4513.6 1750.01  4533.9 1751.96
  4608.4 1751.42  4635.5 1749.91  4737.2 1748.35  4920.1 1751.36  4980.4 1751.41
  4990.4 1750.67  5001.2 1746.78  5001.7 1746.28  5019.7 1746.78  5020.5 1747.73
  5070.5 1749.01  5140.5 1748.88  5209.5 1750.75  5407.4 1750.23  5475.4 1751.72
  5506.3 1750.37  5592.7 1751.08  5741.2 1750.34  5767.4 1750.72  5770.1 1751.62
  5796.3 1750.28  5945.7 1751.41  5963.4 1752.71  6036.5 1751.51  6533.3 1754.53
#Mann=3,-1,0
  4041.9    0.05       0  5001.2    0.05       0  5019.7    0.05       0
Bank Sta=5001.2,5019.7
Exp/Cntr=0.3,0.1

Type RM Length L Ch R = 1,3722,1910,1910,1910
BEGIN DESCRIPTION:
Elm 02 18 3721.75
END DESCRIPTION:
XS GIS Cut Line= 6
      1612442.34      6837140.52      1612256.72      6837797.06
      1612026.41      6838237.06      1611822.67      6838462.50
      1611679.22      6838594.56      1611655.19      6839494.08
#Sta/Elev= 30
  3523.1 1761.12  3759.5 1756.68  3860.4 1752.32  3972.7 1750.26  3998.5 1751.41
  4085.0 1749.90  4175.2 1751.54  4274.2 1750.60  4309.9 1749.09  4326.3 1746.31
  4354.0 1745.91  4370.5 1748.20  4453.1 1748.95  4466.0 1750.31  4651.7 1749.63
  4680.5 1750.74  4710.8 1749.27  4767.6 1750.32  4831.1 1748.51  4894.6 1749.23
  4965.6 1745.56  4979.8 1746.45  4984.7 1744.65  4985.2 1744.15  5003.3 1744.65
  5015.4 1748.12  5036.4 1750.31  5121.5 1748.90  5524.4 1749.83  6100.7 1754.35
#Mann=3,-1,0
  3523.1    0.05       0  4984.7    0.05       0  5003.3    0.05       0
Bank Sta=4984.7,5003.3
Exp/Cntr=0.3,0.1

Type RM Length L Ch R = 1,1812,496,496,496
BEGIN DESCRIPTION:
Elm 02 18 1811.84
END DESCRIPTION:
XS GIS Cut Line= 3
      1611504.96      6837078.83      1611525.79      6837745.49
      1611527.97      6838964.40
#Sta/Elev= 30
  4338.7 1755.78  4598.0 1754.19  4728.1 1752.71  4788.1 1753.03  4816.7 1751.97
  4821.7 1752.65  4828.1 1751.80  4838.1 1749.28  4858.1 1747.44  4888.1 1748.19
  4898.1 1749.79  4908.2 1748.61  4918.2 1746.17  4928.2 1745.34  4978.2 1743.74
  4988.2 1742.15  5008.7 1741.75  5009.2 1741.25  5027.2 1741.25  5027.7 1741.75
  5028.2 1742.35  5048.2 1743.34  5078.2 1747.02  5108.2 1747.42  5358.2 1748.27
  5618.2 1746.77  5868.2 1748.85  6138.2 1749.66  6198.2 1749.23  6224.6 1750.29
#Mann=3,-1,0
  4338.7    0.05       0  5008.7    0.03       0  5027.7    0.05       0
Bank Sta=5008.7,5027.7
Exp/Cntr=0.3,0.1

Type RM Length L Ch R = 1,1316,591,591,591
BEGIN DESCRIPTION:
Elm 02 18 1316.35
END DESCRIPTION:
XS GIS Cut Line= 3
      1611387.79      6836888.68      1611114.34      6837602.26
      1611156.72      6838979.52
#Sta/Elev= 30
  4238.3 1756.21  4396.3 1754.84  4625.9 1751.48  4675.3 1751.35  4705.3 1750.15
  4710.7 1750.54  4735.3 1749.86  4765.4 1748.59  4805.2 1746.03  4869.4 1745.21
  4934.9 1742.90  5002.5 1741.67  5018.7 1740.00  5019.2 1739.50  5037.3 1739.50
  5037.8 1740.00  5038.2 1741.28  5058.3 1745.03  5068.3 1746.32  5118.3 1745.77
  5328.4 1746.27  5478.5 1744.93  5568.5 1745.30  5598.5 1744.63  5738.6 1745.42
  5918.7 1747.30  5968.7 1746.73  6108.7 1747.93  6358.9 1748.23  6380.4 1748.98
#Mann=3,-1,0
  4238.3    0.05       0  5018.7    0.05       0  5037.8    0.05       0
Bank Sta=5018.7,5037.8
Exp/Cntr=0.3,0.1

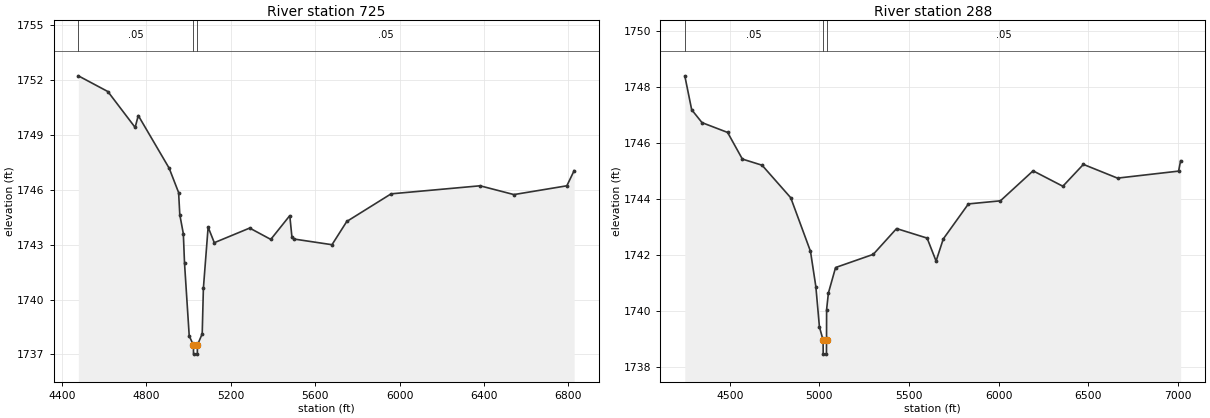
Type RM Length L Ch R = 1,725,437,437,437
BEGIN DESCRIPTION:
Mapping XS 1e28703a
END DESCRIPTION:
XS GIS Cut Line= 5
      1611078.72      6836747.68      1610854.79      6837080.98
      1610714.16      6837362.23      1610719.37      6838133.07
      1610789.68      6838992.46
#Sta/Elev= 30
  4478.0 1752.23  4618.0 1751.37  4747.1 1749.41  4762.0 1750.06  4908.4 1747.18
  4953.1 1745.85  4958.7 1744.64  4975.5 1743.60  4981.1 1741.99  5003.4 1738.01
  5023.2 1737.52  5023.7 1737.02  5041.8 1737.02  5042.3 1737.52  5064.9 1738.13
  5070.5 1740.62  5092.9 1743.96  5122.2 1743.11  5289.8 1743.91  5389.8 1743.29
  5479.8 1744.59  5489.8 1743.44  5499.8 1743.31  5679.8 1743.00  5749.8 1744.27
  5959.8 1745.78  6381.2 1746.22  6541.7 1745.74  6792.5 1746.22  6827.1 1747.05
#Mann=3,-1,0
  4478.0    0.05       0  5023.2    0.05       0  5042.3    0.05       0
Bank Sta=5023.2,5042.3
Exp/Cntr=0.3,0.1

Type RM Length L Ch R = 1,288,0,0,0
BEGIN DESCRIPTION:
Elm 02 18 610.01
END DESCRIPTION:
XS GIS Cut Line= 4
      1610722.83      6836304.10      1610453.74      6836811.89
      1610462.42      6837350.08      1610557.91      6838999.38
#Sta/Elev= 30
  4249.2 1748.39  4287.6 1747.18  4345.2 1746.72  4487.9 1746.37  4570.2 1745.42
  4680.2 1745.20  4840.0 1744.04  4950.0 1742.13  4980.0 1740.87  5000.0 1739.43
  5020.5 1738.96  5021.0 1738.46  5039.1 1738.46  5039.6 1738.96  5040.0 1740.05
  5050.0 1740.64  5090.0 1741.55  5300.1 1742.02  5430.2 1742.94  5600.5 1742.60
  5650.5 1741.78  5690.6 1742.57  5830.8 1743.82  6009.2 1743.93  6191.4 1745.00
  6357.5 1744.45  6471.9 1745.23  6662.2 1744.74  7002.8 1744.99  7014.2 1745.36
#Mann=3,-1,0
  4249.2    0.05       0  5020.5    0.05       0  5039.6    0.05       0
Bank Sta=5020.5,5039.6
Exp/Cntr=0.3,0.1

Chan Stop Cuts=-1