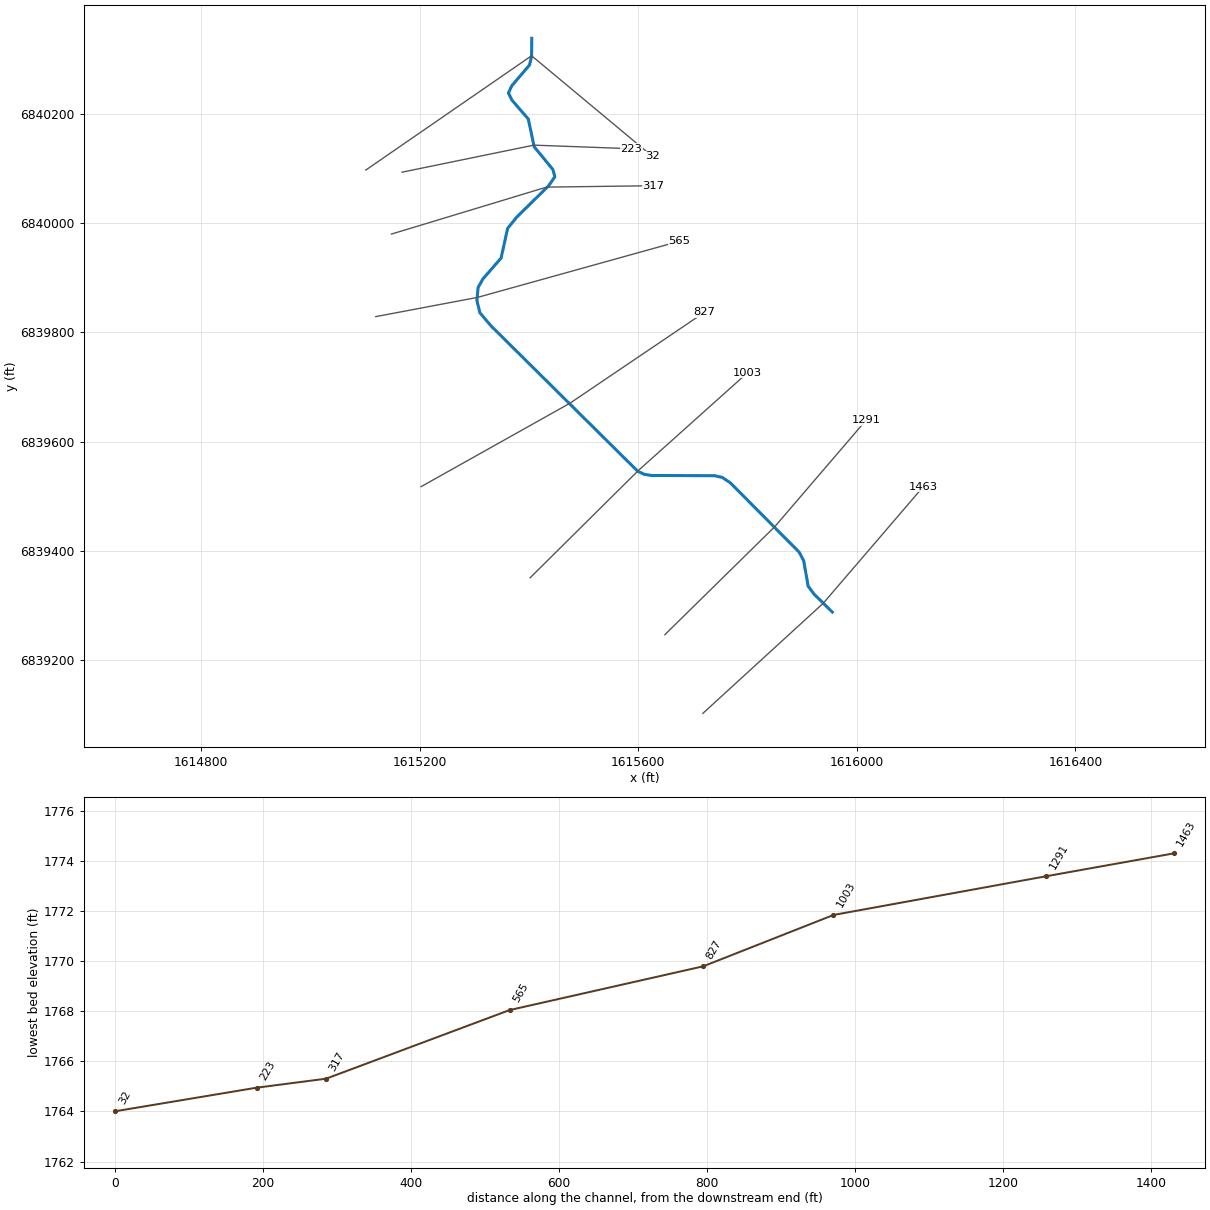
--- Elm 02 20.prj (project) ---

Proj Title=Elm 02 20 Base Level Engineering
Current Plan=p01
Default Exp/Contr=0.3,0.1
English Units
Geom File=g01
Flow File=f01
Plan File=p01
BEGIN DESCRIPTION:
Elm 02 20
END DESCRIPTION:

--- Elm 02 20.p01 (plan) ---

Plan Title=Multiple Run
Short Identifier=Multiple
Geom File=g01
Flow File=f01
Subcritical Flow
K Sum by GR= 0
Std Step Tol= 0.01
Critical Tol= 0.01
Num of Std Step Trials= 20
Max Error Tol= 0.3
Flow Tol Ratio= 0.001
Split Flow NTrial= 30
Split Flow Tol= 0.02
Split Flow Ratio= 0.02
Log Output Level= 0
Friction Slope Method= 1
Unsteady Friction Slope Method= 2
Unsteady Bridges Friction Slope Method= 1
Parabolic Critical Depth
Global Vel Dist=  1 , 1 , 1
Global Log Level= 0
CheckData=True
Encroach Param= -1, 0, 0, 0
BEGIN DESCRIPTION:
Multiple Run
END DESCRIPTION:

--- Elm 02 20.f01 (steady flow) ---

Flow Title=Multiple
Number of Profiles=7
Profile Names=10-year,25-year,50-year,1pct_min,100-year,1pct_plu,500-year
River Rch & RM= Elm 02 20,Reach-1,1463
     104     136     161     118     189     261     266
Boundary for River Rch & Prof#=Elm 02 20,Reach-1,1
Up Type=0
Dn Type=3
Dn Slope=0.001
Boundary for River Rch & Prof#=Elm 02 20,Reach-1,2
Up Type=0
Dn Type=3
Dn Slope=0.001
Boundary for River Rch & Prof#=Elm 02 20,Reach-1,3
Up Type=0
Dn Type=3
Dn Slope=0.001
Boundary for River Rch & Prof#=Elm 02 20,Reach-1,4
Up Type=0
Dn Type=3
Dn Slope=0.001
Boundary for River Rch & Prof#=Elm 02 20,Reach-1,5
Up Type=0
Dn Type=3
Dn Slope=0.001
Boundary for River Rch & Prof#=Elm 02 20,Reach-1,6
Up Type=0
Dn Type=3
Dn Slope=0.001
Boundary for River Rch & Prof#=Elm 02 20,Reach-1,7
Up Type=0
Dn Type=3
Dn Slope=0.001

--- Elm 02 20.g01 (geometry) ---

Geom Title=Existing Conditions

River Reach=Elm 02 20,Reach-1
Reach XY= 30
      1615955.00      6839288.00      1615921.42      6839321.08
      1615910.71      6839335.65      1615902.66      6839382.03
      1615894.30      6839397.71      1615768.32      6839524.63
      1615753.53      6839534.46      1615739.84      6839537.60
      1615624.99      6839537.98      1615610.86      6839540.07
      1615598.81      6839545.82      1615331.04      6839811.18
      1615310.09      6839835.70      1615304.59      6839858.13
      1615306.76      6839881.88      1615315.49      6839897.55
      1615348.82      6839935.81      1615360.86      6839990.30
      1615378.12      6840011.47      1615435.68      6840067.99
      1615447.22      6840084.60      1615443.72      6840097.87
      1615409.40      6840139.65      1615398.65      6840190.29
      1615368.83      6840224.79      1615362.28      6840238.03
      1615368.47      6840251.27      1615401.00      6840289.36
      1615404.69      6840306.12      1615405.00      6840338.00

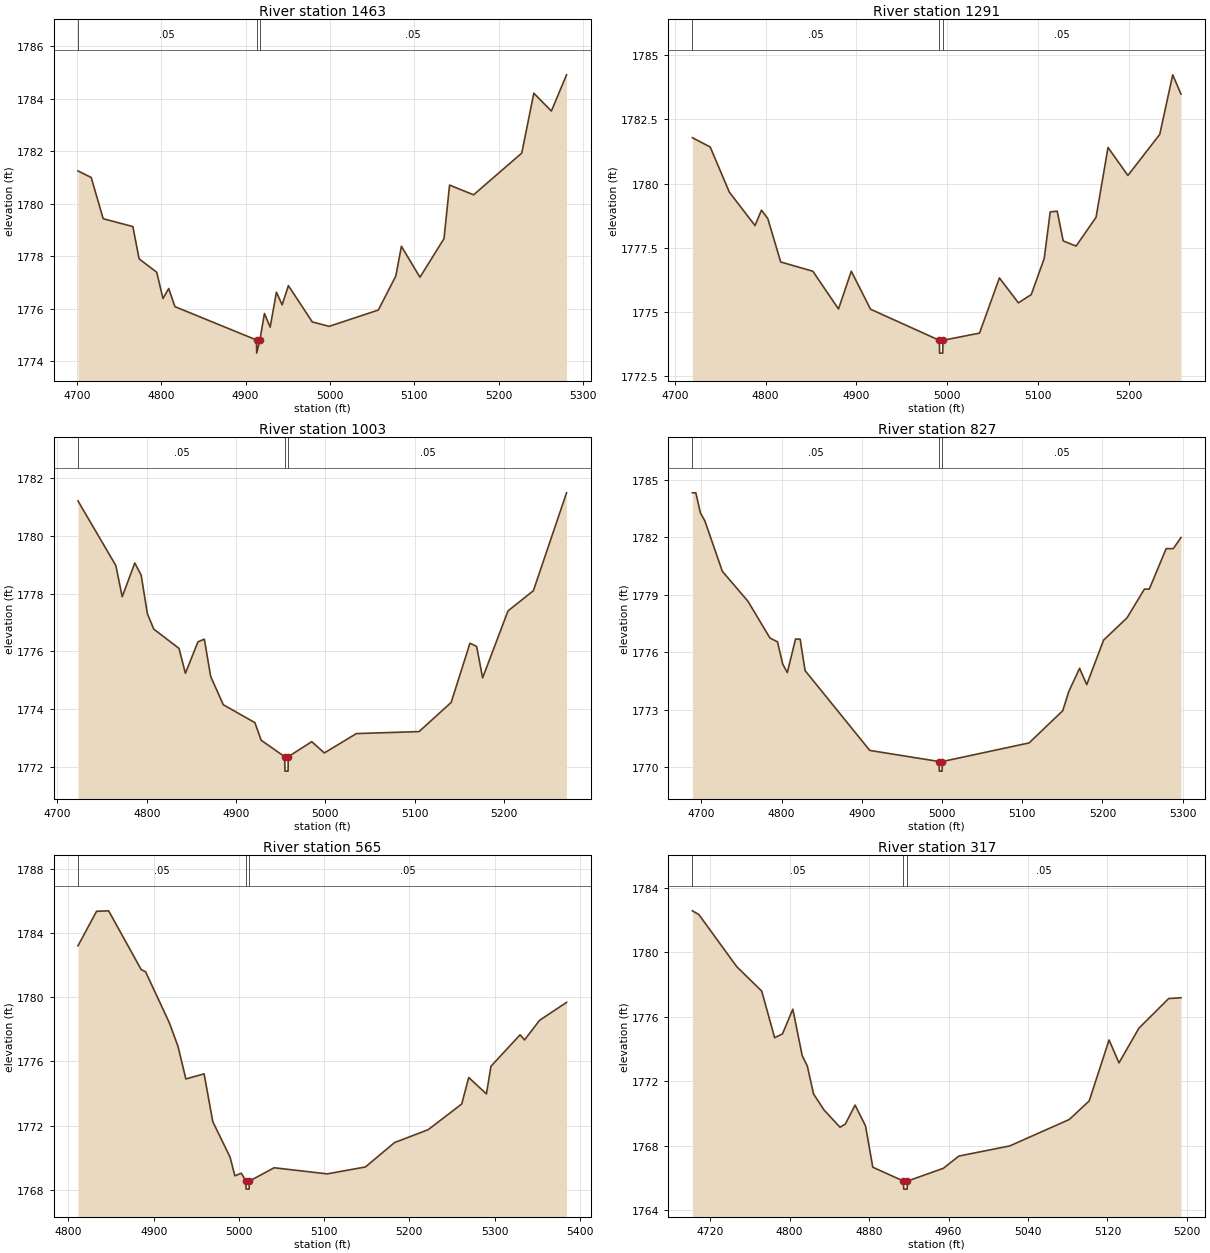
Type RM Length L Ch R = 1,1463,172,172,172
BEGIN DESCRIPTION:
Elm 02 20 1015.899
END DESCRIPTION:
XS GIS Cut Line= 3
      1615718.11      6839102.64      1615938.52      6839304.23
      1616121.24      6839517.19
#Sta/Elev= 30
  4701.3 1781.25  4717.0 1781.00  4731.2 1779.43  4766.4 1779.13  4773.8 1777.90
  4794.7 1777.39  4802.1 1776.39  4808.9 1776.77  4816.3 1776.08  4913.0 1774.81
  4913.2 1774.31  4917.0 1774.81  4922.4 1775.82  4929.2 1775.30  4936.6 1776.63
  4943.4 1776.15  4950.8 1776.88  4979.1 1775.50  4999.1 1775.33  5057.4 1775.95
  5078.2 1777.25  5084.8 1778.38  5106.8 1777.20  5135.3 1778.67  5141.9 1780.71
  5170.4 1780.34  5227.5 1781.93  5241.8 1784.21  5262.6 1783.53  5280.6 1784.91
#Mann=3,-1,0
  4701.3    0.05       0  4913.0    0.05       0  4917.0    0.05       0
Bank Sta=4913,4917
Exp/Cntr=0.3,0.1

Type RM Length L Ch R = 1,1291,288,288,288
BEGIN DESCRIPTION:
Elm 02 20 1291.16
END DESCRIPTION:
XS GIS Cut Line= 3
      1615648.66      6839246.74      1615850.01      6839444.62
      1616016.67      6839639.05
#Sta/Elev= 30
  4719.3 1781.79  4738.9 1781.43  4760.0 1779.67  4788.3 1778.37  4795.4 1778.97
  4802.4 1778.64  4816.6 1776.95  4852.0 1776.59  4880.3 1775.12  4894.4 1776.59
  4915.6 1775.11  4991.4 1773.90  4991.7 1773.40  4995.2 1773.40  4995.4 1773.90
  5035.7 1774.18  5057.6 1776.33  5078.5 1775.36  5092.7 1775.68  5107.0 1777.09
  5113.6 1778.90  5121.3 1778.93  5127.9 1777.77  5142.1 1777.57  5164.1 1778.69
  5177.3 1781.41  5199.2 1780.32  5234.3 1781.92  5248.6 1784.24  5257.7 1783.49
#Mann=3,-1,0
  4719.3    0.05       0  4991.4    0.05       0  4995.4    0.05       0
Bank Sta=4991.4,4995.4
Exp/Cntr=0.3,0.1

Type RM Length L Ch R = 1,1003,176,176,176
BEGIN DESCRIPTION:
Elm 02 20 1002.52
END DESCRIPTION:
XS GIS Cut Line= 3
      1615402.13      6839350.90      1615600.01      6839547.06
      1615799.70      6839725.90
#Sta/Elev= 30
  4723.1 1781.21  4765.5 1778.97  4772.6 1777.89  4786.7 1779.06  4793.8 1778.64
  4800.8 1777.30  4807.9 1776.77  4836.2 1776.10  4843.3 1775.24  4857.4 1776.33
  4864.5 1776.42  4871.6 1775.13  4885.7 1774.15  4921.1 1773.53  4928.1 1772.92
  4954.4 1772.35  4954.7 1771.85  4958.2 1771.85  4958.4 1772.35  4984.7 1772.87
  4998.8 1772.48  5034.6 1773.15  5104.8 1773.22  5140.7 1774.23  5161.7 1776.28
  5169.2 1776.17  5175.9 1775.08  5204.3 1777.40  5232.7 1778.10  5269.8 1781.49
#Mann=3,-1,0
  4723.1    0.05       0  4954.4    0.03       0  4958.4    0.05       0
Bank Sta=4954.4,4958.4
Exp/Cntr=0.3,0.1

Type RM Length L Ch R = 1,827,262,262,262
BEGIN DESCRIPTION:
Elm 02 20 826.61
END DESCRIPTION:
XS GIS Cut Line= 3
      1615202.46      6839517.55      1615475.01      6839670.32
      1615720.78      6839836.47
#Sta/Elev= 30
  4688.9 1784.31  4693.2 1784.31  4698.8 1783.27  4704.5 1782.84  4726.2 1780.22
  4758.1 1778.66  4785.6 1776.74  4795.0 1776.54  4801.5 1775.38  4807.2 1774.94
  4817.5 1776.69  4823.2 1776.68  4829.4 1775.04  4910.0 1770.88  4996.5 1770.30
  4996.7 1769.80  5000.2 1769.80  5000.5 1770.30  5108.6 1771.27  5150.6 1772.95
  5158.2 1773.96  5171.6 1775.16  5180.5 1774.31  5201.5 1776.63  5230.7 1777.79
  5252.4 1779.29  5258.5 1779.29  5279.5 1781.40  5288.4 1781.40  5298.0 1781.98
#Mann=3,-1,0
  4688.9    0.05       0  4996.5    0.03       0  5000.5    0.05       0
Bank Sta=4996.5,5000.5
Exp/Cntr=0.3,0.1

Type RM Length L Ch R = 1,565,248,248,248
BEGIN DESCRIPTION:
Elm 02 20 564.55
END DESCRIPTION:
XS GIS Cut Line= 3
      1615119.59      6839828.75      1615305.74      6839863.90
      1615675.56      6839966.77
#Sta/Elev= 30
  4811.2 1783.20  4833.0 1785.35  4847.2 1785.38  4885.4 1781.72  4890.5 1781.59
  4918.5 1778.40  4928.7 1776.92  4937.8 1774.91  4959.2 1775.23  4969.4 1772.25
  4989.7 1770.04  4995.3 1768.88  5002.9 1769.04  5008.3 1768.55  5008.5 1768.05
  5012.0 1768.05  5012.3 1768.55  5041.4 1769.38  5103.7 1769.00  5148.5 1769.43
  5182.7 1770.95  5222.1 1771.75  5261.5 1773.35  5269.7 1775.00  5290.5 1773.98
  5295.8 1775.70  5330.0 1777.66  5335.2 1777.34  5352.8 1778.56  5384.5 1779.68
#Mann=3,-1,0
  4811.2    0.05       0  5008.3    0.05       0  5012.3    0.05       0
Bank Sta=5008.3,5012.3
Exp/Cntr=0.3,0.1

Type RM Length L Ch R = 1,317,94,94,94
BEGIN DESCRIPTION:
Elm 02 20 317.12
END DESCRIPTION:
XS GIS Cut Line= 3
      1615148.21      6839979.79      1615432.05      6840065.72
      1615627.37      6840068.32
#Sta/Elev= 30
  4702.1 1782.57  4708.6 1782.34  4746.7 1779.11  4771.9 1777.59  4784.9 1774.70
  4792.8 1774.94  4803.2 1776.47  4812.6 1773.60  4817.8 1772.94  4824.1 1771.21
  4834.6 1770.22  4850.7 1769.15  4856.0 1769.34  4865.9 1770.52  4876.4 1769.23
  4883.7 1766.67  4914.6 1765.81  4914.8 1765.31  4918.3 1765.31  4918.6 1765.81
  4954.7 1766.60  4970.4 1767.36  5021.6 1767.99  5081.6 1769.63  5101.6 1770.78
  5121.6 1774.56  5131.6 1773.14  5151.6 1775.29  5181.6 1777.13  5194.0 1777.18
#Mann=3,-1,0
  4702.1    0.05       0  4914.6    0.05       0  4918.6    0.05       0
Bank Sta=4914.6,4918.6
Exp/Cntr=0.3,0.1

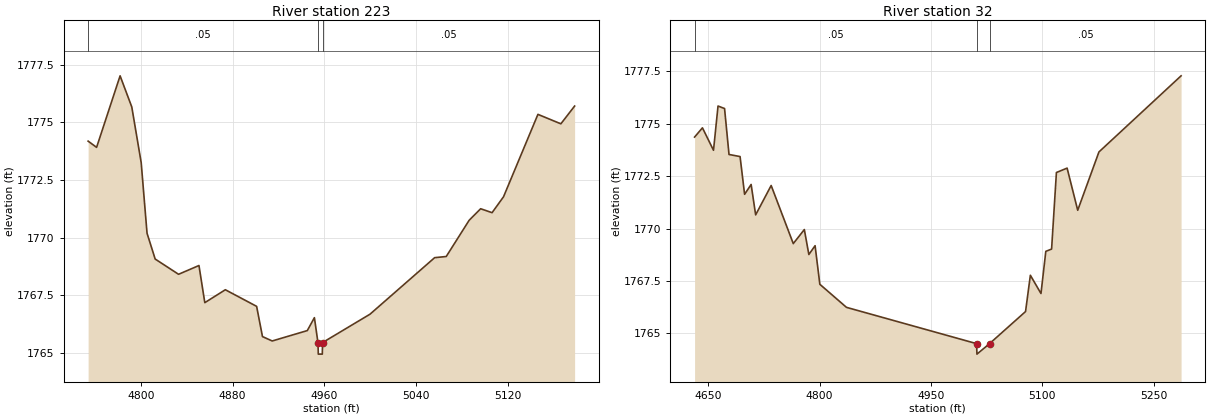
Type RM Length L Ch R = 1,223,191,191,191
BEGIN DESCRIPTION:
Elm 02 20 222.94
END DESCRIPTION:
XS GIS Cut Line= 3
      1615167.72      6840093.06      1615408.61      6840142.54
      1615586.97      6840136.03
#Sta/Elev= 30
  4753.9 1774.18  4761.3 1773.91  4781.8 1777.01  4792.0 1775.66  4800.2 1773.25
  4805.3 1770.19  4812.4 1769.07  4832.8 1768.41  4850.6 1768.79  4855.7 1767.18
  4873.6 1767.74  4900.9 1767.02  4906.0 1765.71  4914.5 1765.52  4945.1 1765.97
  4951.3 1766.53  4954.4 1765.45  4954.7 1764.95  4958.2 1764.95  4958.4 1765.45
  4999.8 1766.68  5056.2 1769.13  5066.3 1769.18  5086.3 1770.75  5096.3 1771.25
  5106.3 1771.08  5116.3 1771.77  5146.3 1775.34  5166.3 1774.93  5178.3 1775.70
#Mann=3,-1,0
  4753.9    0.05       0  4954.4    0.05       0  4958.4    0.05       0
Bank Sta=4954.4,4958.4
Exp/Cntr=0.3,0.1

Type RM Length L Ch R = 1,32,0,0,0
BEGIN DESCRIPTION:
Elm 02 20 528.436
END DESCRIPTION:
XS GIS Cut Line= 3
      1615101.30      6840096.96      1615404.69      6840306.12
      1615625.28      6840122.36
#Sta/Elev= 30
  4631.5 1774.36  4642.1 1774.80  4657.0 1773.73  4663.1 1775.84  4671.9 1775.72
  4677.9 1773.53  4692.8 1773.43  4698.9 1771.63  4707.7 1772.10  4713.8 1770.65
  4734.7 1772.05  4764.5 1769.28  4779.4 1769.95  4785.5 1768.76  4793.9 1769.18
  4800.3 1767.34  4836.2 1766.24  5011.5 1764.51  5012.0 1764.01  5029.0 1764.51
  5077.5 1766.04  5084.0 1767.77  5098.3 1766.90  5104.8 1768.91  5112.6 1769.02
  5119.1 1772.67  5133.5 1772.88  5147.8 1770.87  5176.4 1773.65  5287.1 1777.28
#Mann=3,-1,0
  4631.5    0.05       0  5011.5    0.05       0  5029.0    0.05       0
Bank Sta=5011.5,5029
Exp/Cntr=0.3,0.1

Chan Stop Cuts=-1