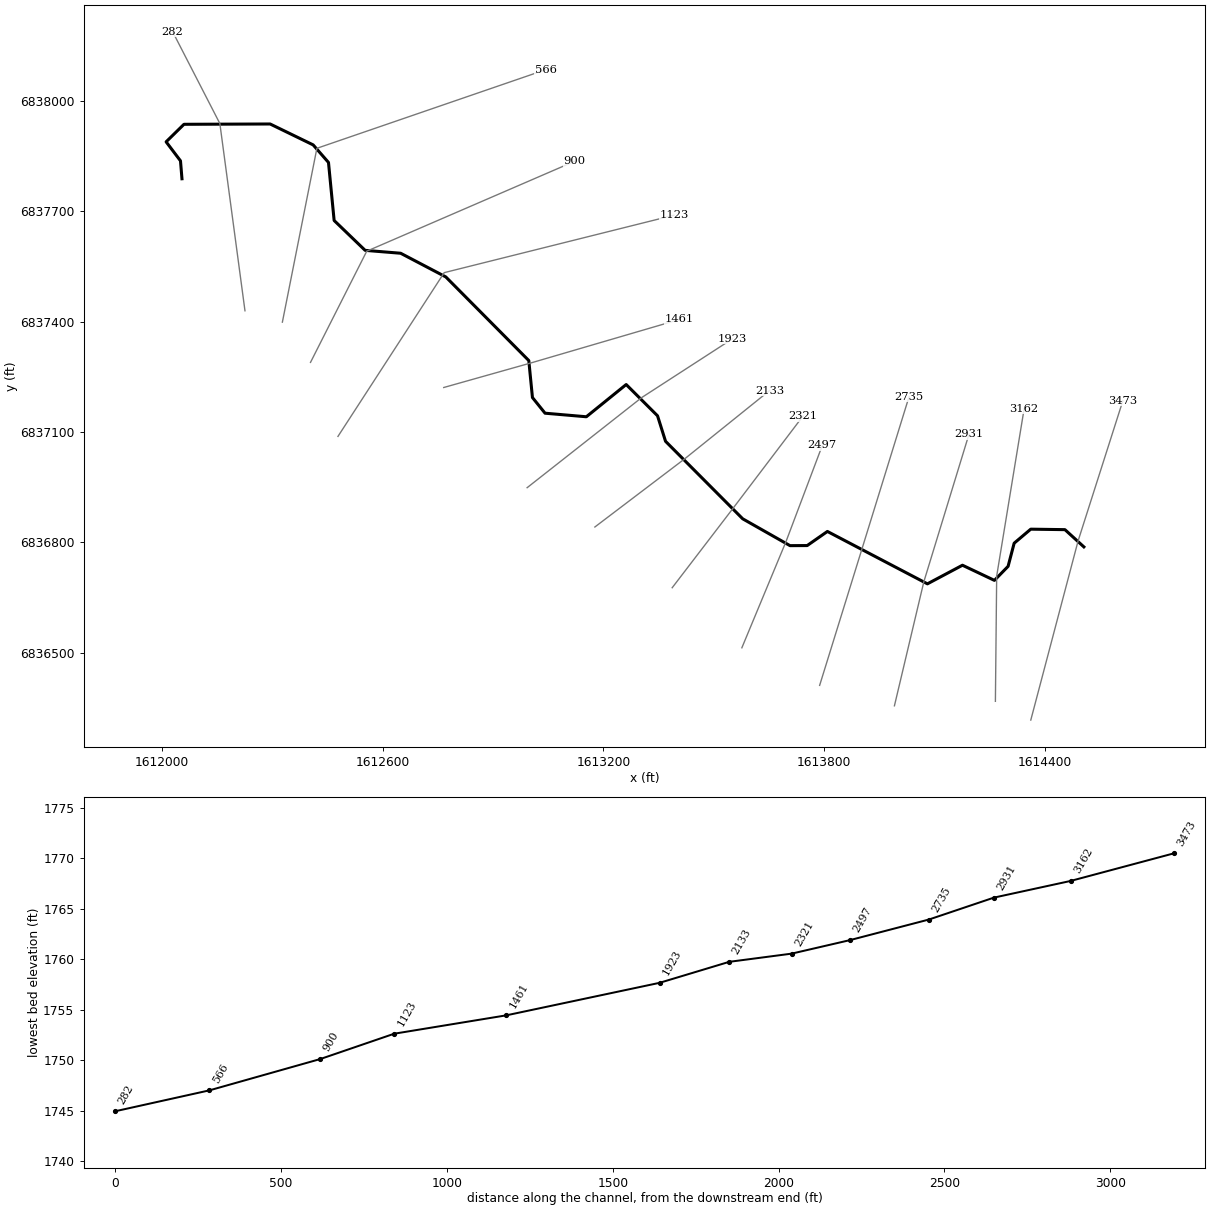
--- Elm 02 21.prj (project) ---

Proj Title=Elm 02 21 Base Level Engineering
Current Plan=p01
Default Exp/Contr=0.3,0.1
English Units
Geom File=g01
Flow File=f01
Plan File=p01
BEGIN DESCRIPTION:
Elm 02 21
END DESCRIPTION:

--- Elm 02 21.p01 (plan) ---

Plan Title=Multiple Run
Short Identifier=Multiple
Geom File=g01
Flow File=f01
Subcritical Flow
K Sum by GR= 0
Std Step Tol= 0.01
Critical Tol= 0.01
Num of Std Step Trials= 20
Max Error Tol= 0.3
Flow Tol Ratio= 0.001
Split Flow NTrial= 30
Split Flow Tol= 0.02
Split Flow Ratio= 0.02
Log Output Level= 0
Friction Slope Method= 1
Unsteady Friction Slope Method= 2
Unsteady Bridges Friction Slope Method= 1
Parabolic Critical Depth
Global Vel Dist=  1 , 1 , 1
Global Log Level= 0
CheckData=True
Encroach Param= -1, 0, 0, 0
BEGIN DESCRIPTION:
Multiple Run
END DESCRIPTION:

--- Elm 02 21.f01 (steady flow) ---

Flow Title=Multiple
Number of Profiles=7
Profile Names=10-year,25-year,50-year,1pct_min,100-year,1pct_plu,500-year
River Rch & RM= Elm 02 21,Reach-1,3473
     103     136     161     119     191     263     272
Boundary for River Rch & Prof#=Elm 02 21,Reach-1,1
Up Type=0
Dn Type=3
Dn Slope=0.001
Boundary for River Rch & Prof#=Elm 02 21,Reach-1,2
Up Type=0
Dn Type=3
Dn Slope=0.001
Boundary for River Rch & Prof#=Elm 02 21,Reach-1,3
Up Type=0
Dn Type=3
Dn Slope=0.001
Boundary for River Rch & Prof#=Elm 02 21,Reach-1,4
Up Type=0
Dn Type=3
Dn Slope=0.001
Boundary for River Rch & Prof#=Elm 02 21,Reach-1,5
Up Type=0
Dn Type=3
Dn Slope=0.001
Boundary for River Rch & Prof#=Elm 02 21,Reach-1,6
Up Type=0
Dn Type=3
Dn Slope=0.001
Boundary for River Rch & Prof#=Elm 02 21,Reach-1,7
Up Type=0
Dn Type=3
Dn Slope=0.001

--- Elm 02 21.g01 (geometry) ---

Geom Title=Existing Conditions

River Reach=Elm 02 21,Reach-1
Reach XY= 30
      1614505.00      6836788.00      1614453.59      6836834.82
      1614360.69      6836836.13      1614315.62      6836798.03
      1614299.14      6836735.18      1614262.01      6836697.03
      1614175.21      6836738.19      1614080.00      6836687.60
      1613808.31      6836829.93      1613753.36      6836791.60
      1613706.73      6836791.37      1613578.18      6836864.29
      1613368.63      6837074.79      1613346.84      6837144.09
      1613261.69      6837229.05      1613153.50      6837141.48
      1613041.28      6837151.16      1613007.07      6837193.68
      1612997.14      6837294.17      1612771.68      6837521.36
      1612649.03      6837585.67      1612552.56      6837593.52
      1612468.36      6837674.65      1612453.01      6837832.33
      1612411.39      6837880.00      1612294.50      6837936.80
      1612060.45      6837935.95      1612011.94      6837888.33
      1612050.97      6837836.66      1612055.00      6837788.00

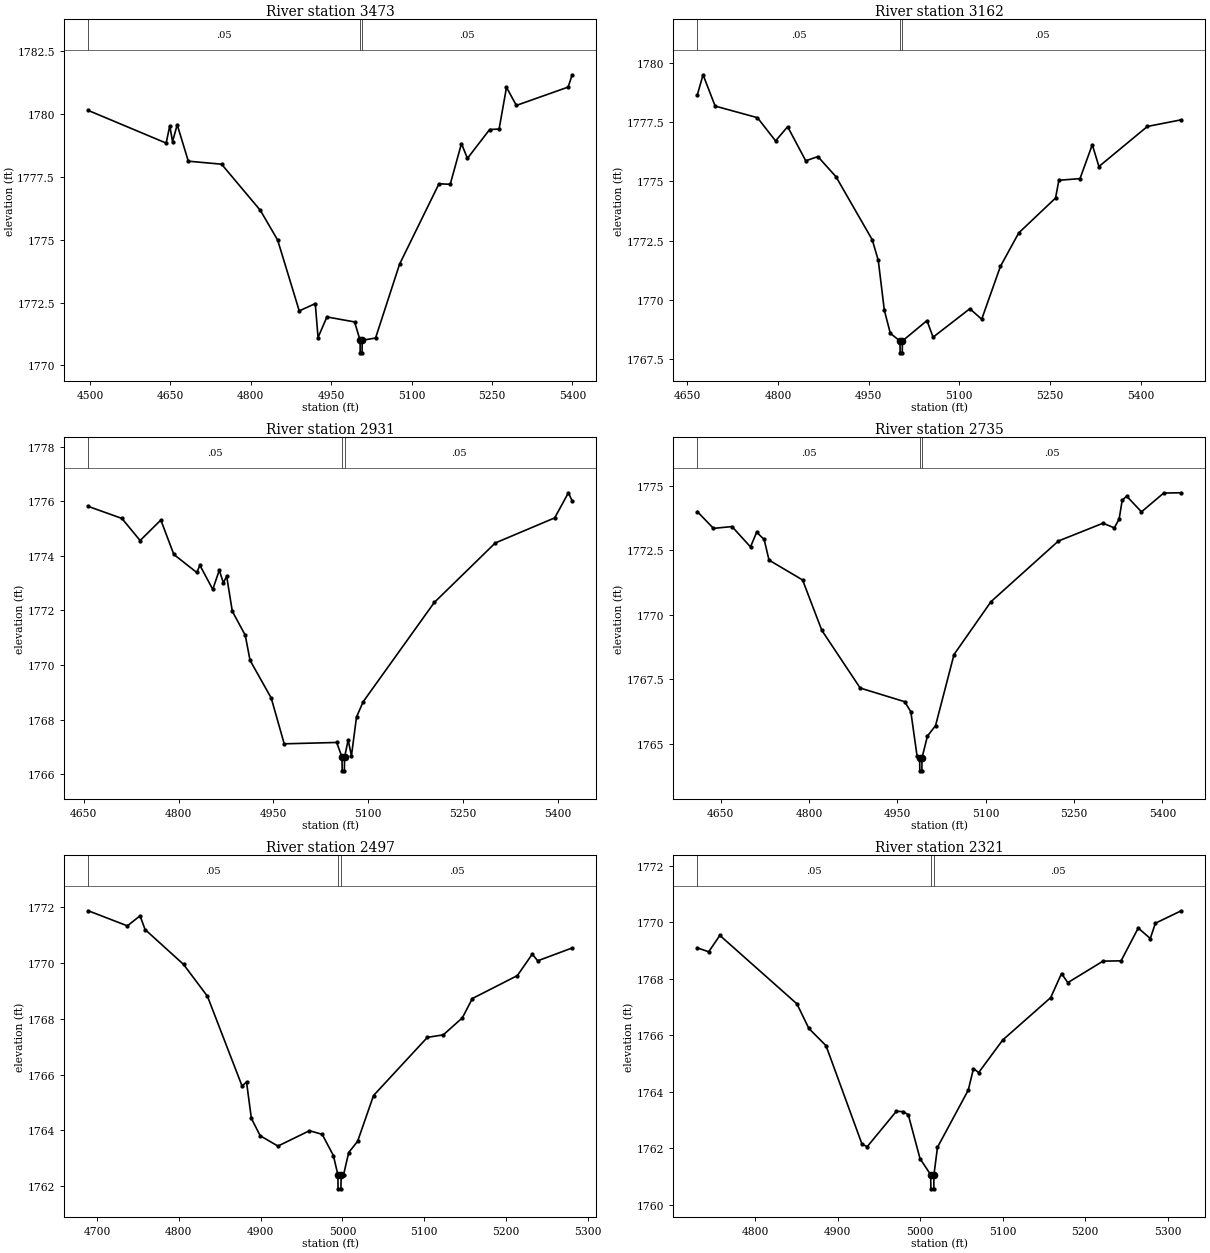
Type RM Length L Ch R = 1,3473,311,311,311
BEGIN DESCRIPTION:
Elm 02 21 3332.843
END DESCRIPTION:
XS GIS Cut Line= 3
      1614360.80      6836317.55      1614489.31      6836804.17
      1614610.85      6837184.84
#Sta/Elev= 30
  4496.7 1780.15  4642.0 1778.85  4648.7 1779.54  4653.9 1778.91  4662.6 1779.58
  4683.3 1778.13  4745.4 1778.01  4817.8 1776.17  4850.0 1774.99  4890.3 1772.17
  4920.2 1772.46  4925.4 1771.11  4941.9 1771.93  4993.6 1771.73  5003.8 1771.00
  5004.0 1770.50  5007.5 1770.50  5007.8 1771.00  5032.7 1771.09  5077.5 1774.03
  5151.0 1777.23  5172.0 1777.21  5193.0 1778.83  5204.1 1778.24  5245.5 1779.39
  5263.2 1779.41  5277.0 1781.07  5295.4 1780.35  5392.0 1781.08  5399.6 1781.57
#Mann=3,-1,0
  4496.7    0.05       0  5003.8    0.05       0  5007.8    0.05       0
Bank Sta=5003.8,5007.8
Exp/Cntr=0.3,0.1

Type RM Length L Ch R = 1,3162,231,231,231
BEGIN DESCRIPTION:
Elm 02 21 3162.09
END DESCRIPTION:
XS GIS Cut Line= 3
      1614264.66      6836368.47      1614268.14      6836708.71
      1614342.74      6837163.27
#Sta/Elev= 30
  4666.4 1778.65  4675.9 1779.50  4695.9 1778.18  4765.9 1777.69  4795.9 1776.71
  4815.9 1777.31  4845.9 1775.87  4865.9 1776.05  4895.9 1775.20  4955.9 1772.54
  4965.9 1771.67  4975.9 1769.57  4985.9 1768.59  5001.8 1768.27  5002.1 1767.77
  5005.6 1767.77  5005.8 1768.27  5046.5 1769.13  5056.6 1768.43  5117.4 1769.63
  5137.1 1769.19  5168.1 1771.42  5198.4 1772.83  5259.3 1774.30  5264.8 1775.05
  5299.8 1775.12  5320.1 1776.55  5331.1 1775.63  5411.3 1777.32  5467.3 1777.60
#Mann=3,-1,0
  4666.4    0.05       0  5001.8    0.05       0  5005.8    0.05       0
Bank Sta=5001.8,5005.8
Exp/Cntr=0.3,0.1

Type RM Length L Ch R = 1,2931,196,196,196
BEGIN DESCRIPTION:
Elm 02 21 2931.43
END DESCRIPTION:
XS GIS Cut Line= 3
      1613990.36      6836356.27      1614070.22      6836693.08
      1614193.05      6837094.46
#Sta/Elev= 30
  4657.2 1775.81  4710.4 1775.37  4739.2 1774.56  4772.0 1775.31  4792.6 1774.05
  4828.8 1773.39  4833.9 1773.65  4854.2 1772.77  4864.5 1773.47  4871.0 1773.01
  4876.2 1773.25  4885.1 1771.97  4905.6 1771.09  4913.2 1770.17  4946.7 1768.79
  4967.3 1767.11  5050.3 1767.16  5058.8 1766.62  5059.0 1766.12  5062.5 1766.12
  5062.8 1766.62  5068.5 1767.25  5073.7 1766.67  5081.7 1768.09  5092.2 1768.65
  5204.8 1772.29  5301.3 1774.47  5395.4 1775.39  5417.1 1776.31  5423.1 1776.01
#Mann=3,-1,0
  4657.2    0.05       0  5058.8    0.05       0  5062.8    0.05       0
Bank Sta=5058.8,5062.8
Exp/Cntr=0.3,0.1

Type RM Length L Ch R = 1,2735,238,238,238
BEGIN DESCRIPTION:
Elm 02 21 2734.82
END DESCRIPTION:
XS GIS Cut Line= 3
      1613787.22      6836411.79      1613903.55      6836786.83
      1614030.28      6837196.51
#Sta/Elev= 30
  4610.3 1774.00  4637.7 1773.35  4669.2 1773.42  4700.6 1772.63  4711.0 1773.20
  4723.8 1772.92  4732.0 1772.12  4789.0 1771.35  4821.6 1769.40  4886.8 1767.16
  4962.4 1766.63  4972.8 1766.24  4983.3 1764.53  4987.7 1764.45  4988.0 1763.95
  4991.5 1763.95  4991.7 1764.45  5001.0 1765.30  5014.7 1765.70  5046.1 1768.46
  5108.9 1770.51  5223.3 1772.86  5299.0 1773.55  5318.2 1773.37  5326.4 1773.71
  5331.6 1774.44  5339.2 1774.60  5364.3 1773.99  5402.1 1774.72  5431.8 1774.73
#Mann=3,-1,0
  4610.3    0.05       0  4987.7    0.05       0  4991.7    0.05       0
Bank Sta=4987.7,4991.7
Exp/Cntr=0.3,0.1

Type RM Length L Ch R = 1,2497,176,176,176
BEGIN DESCRIPTION:
Elm 02 21 2496.72
END DESCRIPTION:
XS GIS Cut Line= 3
      1613575.94      6836513.89      1613695.74      6836802.11
      1613794.47      6837063.67
#Sta/Elev= 30
  4689.3 1771.86  4737.1 1771.32  4752.6 1771.68  4758.7 1771.19  4805.8 1769.94
  4835.0 1768.80  4877.3 1765.59  4882.8 1765.73  4888.7 1764.43  4899.5 1763.81
  4921.2 1763.44  4959.7 1763.99  4975.3 1763.86  4989.0 1763.10  4994.5 1762.41
  4994.7 1761.91  4998.2 1761.91  4998.5 1762.41  5001.4 1762.41  5007.7 1763.21
  5018.6 1763.61  5038.1 1765.25  5103.9 1767.33  5123.4 1767.42  5146.7 1768.03
  5158.9 1768.72  5213.9 1769.54  5232.2 1770.31  5238.8 1770.07  5281.0 1770.53
#Mann=3,-1,0
  4689.3    0.05       0  4994.5    0.05       0  4998.5    0.05       0
Bank Sta=4994.5,4998.5
Exp/Cntr=0.3,0.1

Type RM Length L Ch R = 1,2321,188,188,188
BEGIN DESCRIPTION:
Elm 02 21 2321.42
END DESCRIPTION:
XS GIS Cut Line= 3
      1613386.69      6836677.08      1613551.64      6836892.39
      1613742.19      6837143.56
#Sta/Elev= 30
  4729.8 1769.09  4743.6 1768.95  4757.1 1769.53  4850.5 1767.11  4865.0 1766.24
  4885.8 1765.63  4929.4 1762.15  4935.7 1762.06  4971.0 1763.31  4979.2 1763.30
  4985.5 1763.19  4999.7 1761.64  5012.6 1761.07  5012.9 1760.57  5016.4 1760.57
  5016.6 1761.07  5020.9 1762.04  5058.2 1764.06  5064.5 1764.82  5070.8 1764.68
  5099.9 1765.83  5158.1 1767.33  5171.2 1768.18  5178.9 1767.86  5221.5 1768.62
  5243.4 1768.63  5264.2 1769.79  5278.8 1769.42  5285.0 1769.96  5316.3 1770.40
#Mann=3,-1,0
  4729.8    0.05       0  5012.6    0.05       0  5016.6    0.05       0
Bank Sta=5012.6,5016.6
Exp/Cntr=0.3,0.1

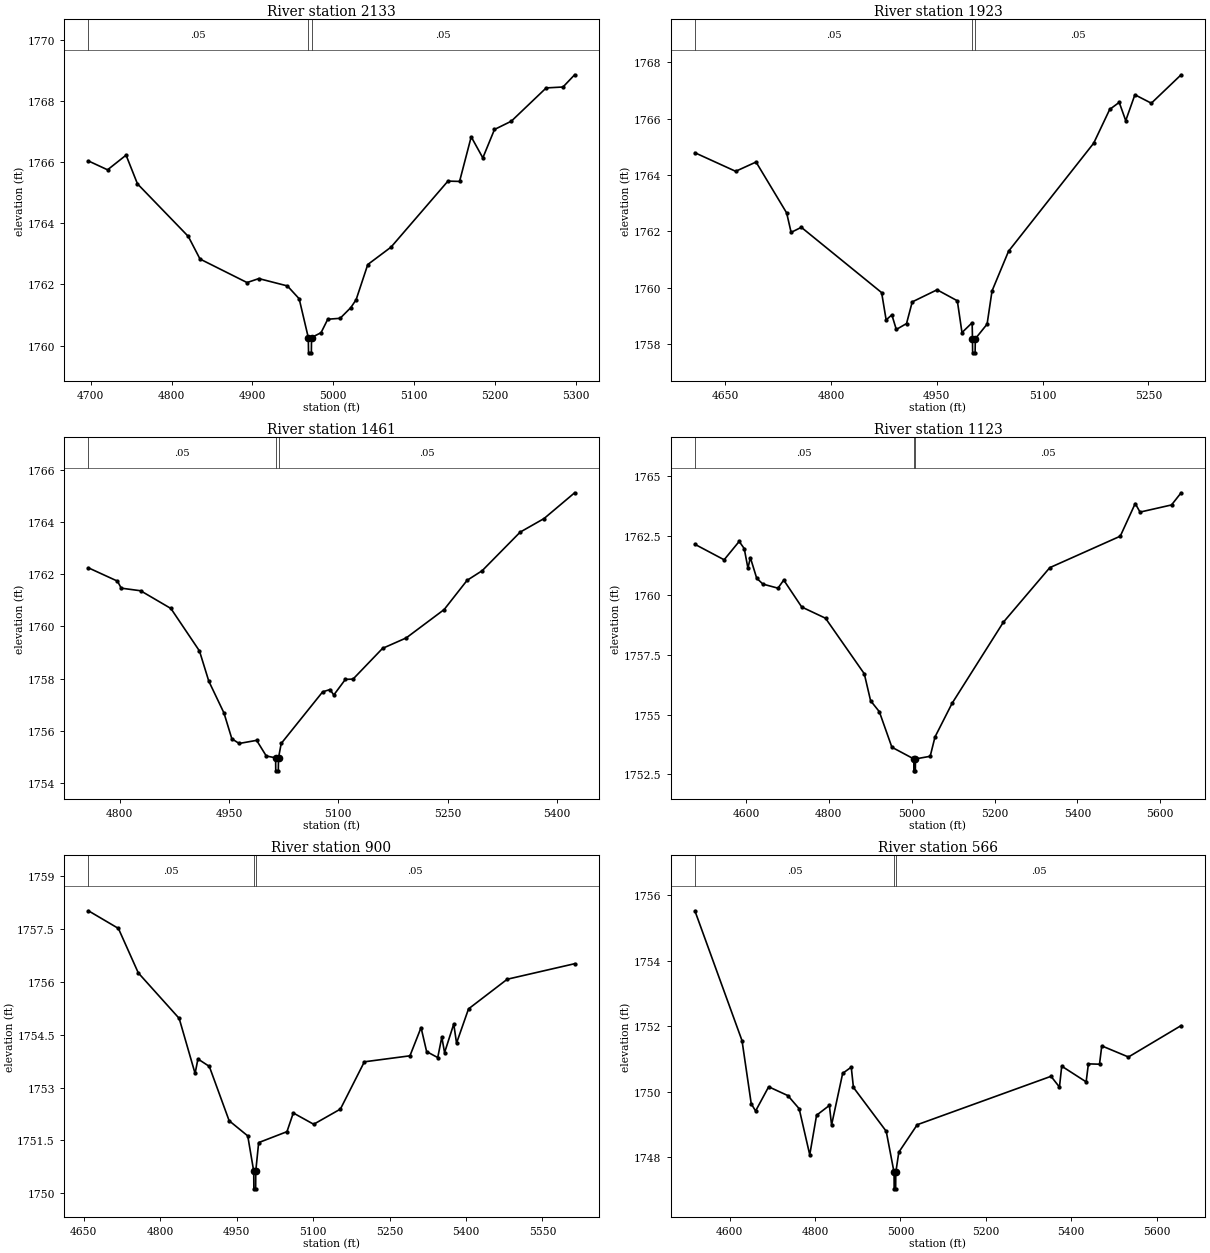
Type RM Length L Ch R = 1,2133,210,210,210
BEGIN DESCRIPTION:
Elm 02 21 2132.88
END DESCRIPTION:
XS GIS Cut Line= 3
      1613176.63      6836842.03      1613421.43      6837027.80
      1613650.81      6837212.34
#Sta/Elev= 30
  4697.0 1766.04  4720.7 1765.75  4743.6 1766.23  4757.7 1765.29  4820.6 1763.57
  4835.1 1762.83  4893.3 1762.06  4907.9 1762.19  4943.2 1761.95  4957.8 1761.53
  4969.1 1760.26  4969.4 1759.76  4972.9 1759.76  4973.1 1760.26  4984.9 1760.42
  4993.2 1760.86  5008.5 1760.89  5021.7 1761.24  5028.3 1761.50  5042.7 1762.65
  5071.5 1763.22  5141.9 1765.38  5156.3 1765.37  5170.7 1766.83  5185.1 1766.14
  5199.5 1767.07  5220.3 1767.34  5263.5 1768.43  5284.3 1768.46  5298.7 1768.86
#Mann=3,-1,0
  4697.0    0.05       0  4969.1    0.05       0  4973.1    0.05       0
Bank Sta=4969.1,4973.1
Exp/Cntr=0.3,0.1

Type RM Length L Ch R = 1,1923,462,462,462
BEGIN DESCRIPTION:
Elm 02 21 1923.31
END DESCRIPTION:
XS GIS Cut Line= 3
      1612992.61      6836948.80      1613303.81      6837193.60
      1613549.98      6837352.96
#Sta/Elev= 30
  4607.1 1764.79  4664.9 1764.13  4693.8 1764.46  4737.2 1762.65  4743.5 1761.96
  4758.0 1762.14  4871.8 1759.82  4878.2 1758.85  4886.3 1759.03  4892.6 1758.51
  4907.1 1758.72  4915.2 1759.49  4950.4 1759.92  4979.1 1759.53  4985.7 1758.40
  5000.1 1758.75  5000.6 1758.18  5000.8 1757.68  5004.3 1757.68  5004.6 1758.18
  5021.3 1758.70  5028.3 1759.88  5051.7 1761.29  5172.4 1765.13  5195.1 1766.33
  5208.6 1766.58  5217.8 1765.93  5230.8 1766.85  5254.1 1766.55  5296.3 1767.56
#Mann=3,-1,0
  4607.1    0.05       0  5000.6    0.05       0  5004.6    0.05       0
Bank Sta=5000.6,5004.6
Exp/Cntr=0.3,0.1

Type RM Length L Ch R = 1,1461,338,338,338
BEGIN DESCRIPTION:
Elm 02 21 1460.86
END DESCRIPTION:
XS GIS Cut Line= 3
      1612766.07      6837220.95      1613001.73      6837287.35
      1613406.71      6837405.85
#Sta/Elev= 30
  4757.3 1762.25  4797.1 1761.74  4802.3 1761.47  4828.9 1761.37  4870.4 1760.69
  4909.6 1759.06  4922.4 1757.90  4943.2 1756.68  4954.0 1755.69  4964.0 1755.51
  4988.0 1755.63  5001.2 1755.03  5014.0 1754.96  5014.2 1754.46  5017.7 1754.46
  5018.0 1754.96  5021.7 1755.51  5078.5 1757.49  5088.6 1757.58  5093.8 1757.37
  5109.7 1757.97  5120.2 1757.98  5160.7 1759.16  5193.1 1759.56  5245.2 1760.65
  5276.6 1761.77  5297.3 1762.14  5349.4 1763.62  5382.1 1764.14  5424.1 1765.13
#Mann=3,-1,0
  4757.3    0.05       0  5014.0    0.05       0  5018.0    0.05       0
Bank Sta=5014,5018
Exp/Cntr=0.3,0.1

Type RM Length L Ch R = 1,1123,223,223,223
BEGIN DESCRIPTION:
Elm 02 21 1123.02
END DESCRIPTION:
XS GIS Cut Line= 3
      1612478.74      6837088.11      1612767.35      6837532.97
      1613391.18      6837688.92
#Sta/Elev= 30
  4476.8 1762.14  4547.4 1761.49  4583.7 1762.26  4595.9 1761.96  4604.8 1761.14
  4610.7 1761.58  4625.9 1760.72  4641.0 1760.47  4677.3 1760.30  4691.2 1760.64
  4734.6 1759.51  4792.0 1759.04  4885.6 1756.71  4900.8 1755.58  4921.9 1755.12
  4952.2 1753.63  5005.1 1753.14  5005.3 1752.64  5008.8 1752.64  5009.1 1753.14
  5044.6 1753.25  5056.2 1754.06  5097.4 1755.47  5221.1 1758.87  5333.2 1761.16
  5503.3 1762.48  5539.4 1763.85  5551.0 1763.49  5627.0 1763.79  5650.1 1764.30
#Mann=3,-1,0
  4476.8    0.05       0  5005.1    0.05       0  5009.1    0.05       0
Bank Sta=5005.1,5009.1
Exp/Cntr=0.3,0.1

Type RM Length L Ch R = 1,900,334,334,334
BEGIN DESCRIPTION:
Elm 02 21 900.11
END DESCRIPTION:
XS GIS Cut Line= 3
      1612404.16      6837289.17      1612556.93      6837591.24
      1613121.48      6837835.41
#Sta/Elev= 30
  4659.5 1758.01  4718.3 1757.51  4757.3 1756.25  4837.5 1754.96  4868.7 1753.40
  4874.3 1753.81  4896.6 1753.60  4935.5 1752.06  4972.0 1751.63  4983.7 1750.63
  4984.0 1750.13  4987.5 1750.13  4987.7 1750.63  4993.4 1751.44  5048.9 1751.75
  5061.3 1752.28  5101.3 1751.96  5153.7 1752.39  5200.7 1753.73  5290.1 1753.90
  5311.9 1754.70  5322.8 1754.02  5344.6 1753.85  5352.6 1754.43  5358.0 1753.99
  5376.0 1754.80  5381.5 1754.26  5405.0 1755.23  5480.9 1756.07  5613.1 1756.51
#Mann=3,-1,0
  4659.5    0.05       0  4983.7    0.05       0  4987.7    0.05       0
Bank Sta=4983.7,4987.7
Exp/Cntr=0.3,0.1

Type RM Length L Ch R = 1,566,284,284,284
BEGIN DESCRIPTION:
Elm 02 21 565.56
END DESCRIPTION:
XS GIS Cut Line= 3
      1612327.76      6837398.50      1612421.51      6837870.75
      1613043.08      6838084.31
#Sta/Elev= 30
  4518.7 1755.53  4629.1 1751.56  4650.7 1749.63  4660.9 1749.41  4691.5 1750.15
  4736.5 1749.88  4762.9 1749.48  4787.7 1748.07  4803.7 1749.28  4833.7 1749.58
  4838.8 1748.98  4864.8 1750.56  4884.9 1750.75  4890.0 1750.13  4966.8 1748.79
  4985.2 1747.53  4985.4 1747.03  4988.9 1747.03  4989.2 1747.53  4996.3 1748.15
  5039.4 1748.99  5352.8 1750.47  5372.5 1750.14  5377.8 1750.78  5435.0 1750.30
  5440.3 1750.85  5466.3 1750.84  5471.6 1751.40  5534.1 1751.06  5657.4 1752.02
#Mann=3,-1,0
  4518.7    0.05       0  4985.2    0.05       0  4989.2    0.05       0
Bank Sta=4985.2,4989.2
Exp/Cntr=0.3,0.1

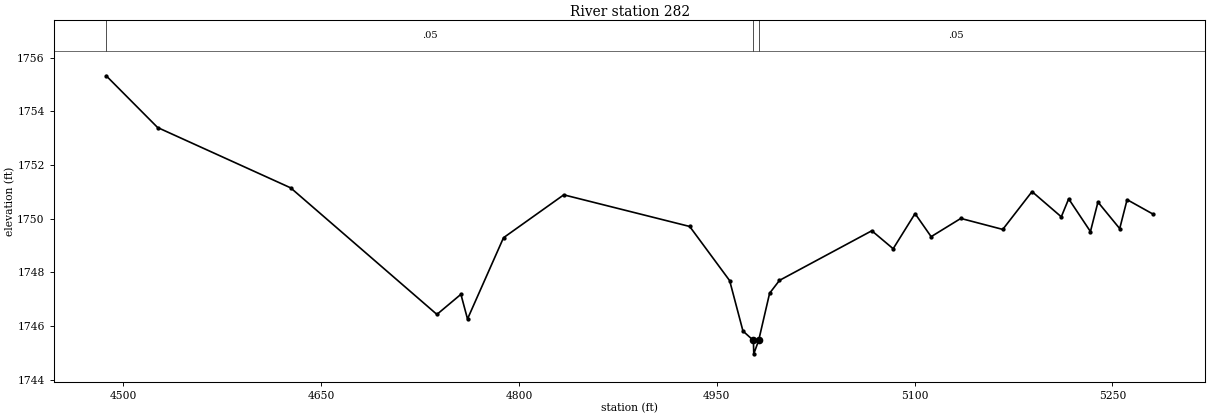
Type RM Length L Ch R = 1,282,0,0,0
BEGIN DESCRIPTION:
Elm 02 21 2850.486
END DESCRIPTION:
XS GIS Cut Line= 3
      1612226.15      6837429.38      1612157.95      6837937.93
      1612029.56      6838187.66
#Sta/Elev= 30
  4486.9 1755.33  4525.9 1753.40  4626.8 1751.15  4737.7 1746.43  4755.9 1747.18
  4760.9 1746.26  4788.2 1749.29  4833.9 1750.89  4929.4 1749.71  4959.7 1747.69
  4969.8 1745.81  4977.7 1745.46  4978.0 1744.96  4981.7 1745.46  4990.0 1747.22
  4997.5 1747.70  5067.5 1749.55  5083.7 1748.88  5100.3 1750.19  5112.5 1749.33
  5135.0 1750.01  5166.8 1749.60  5189.0 1751.01  5211.2 1750.07  5216.8 1750.74
  5233.3 1749.52  5239.0 1750.62  5255.5 1749.63  5261.1 1750.71  5280.8 1750.17
#Mann=3,-1,0
  4486.9    0.05       0  4977.7    0.05       0  4981.7    0.05       0
Bank Sta=4977.7,4981.7
Exp/Cntr=0.3,0.1

Chan Stop Cuts=-1