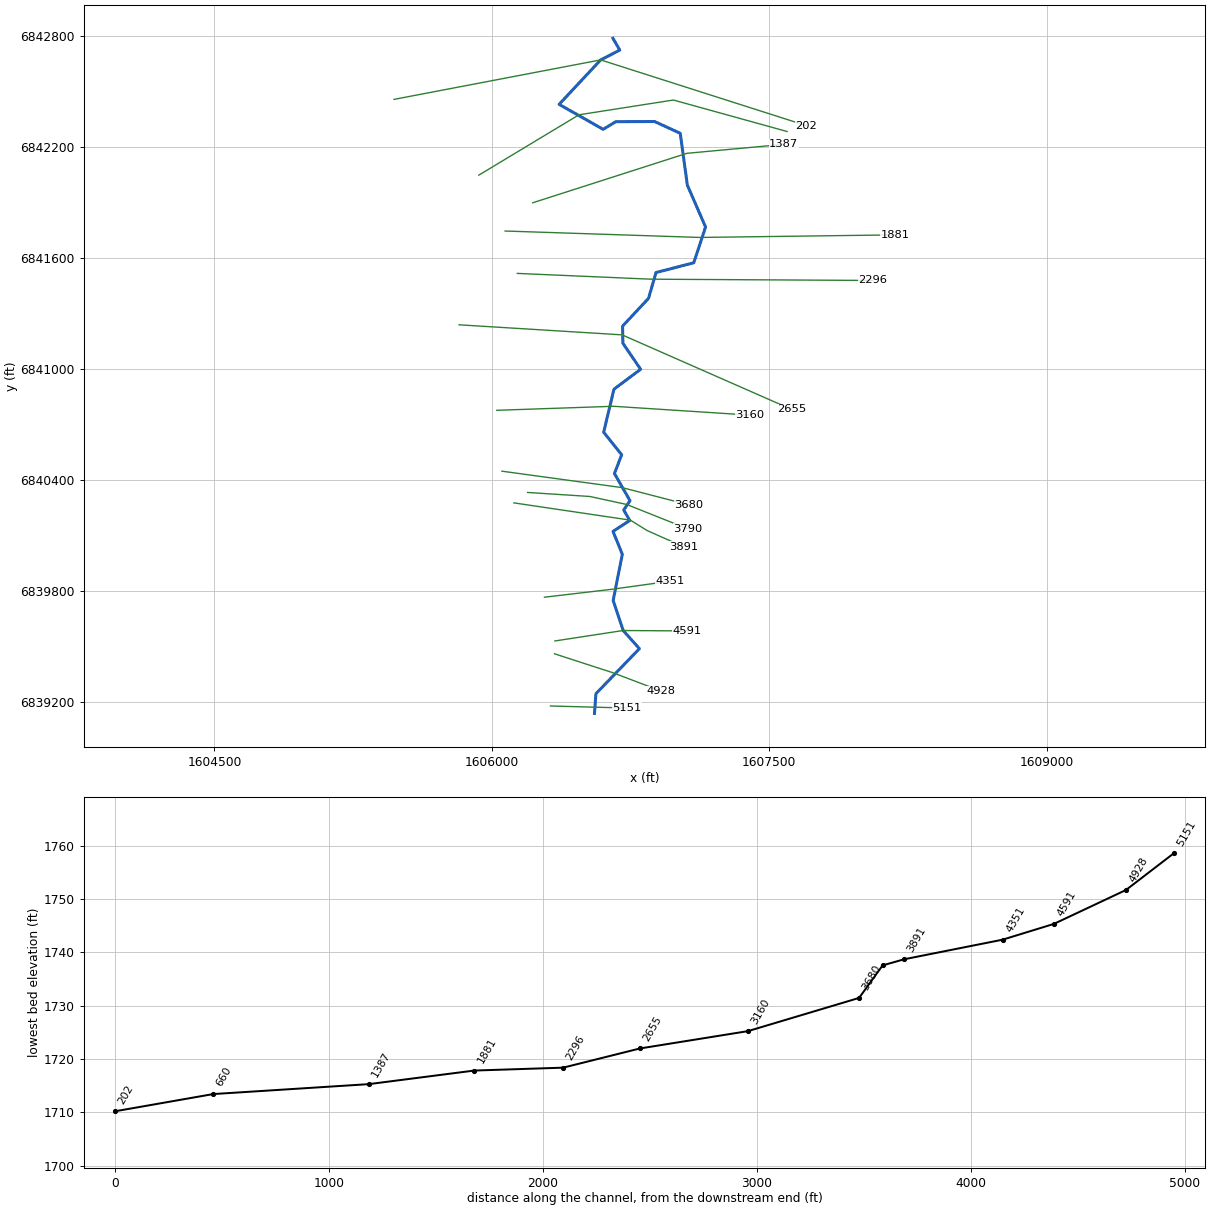
--- Elm 02 22.prj (project) ---

Proj Title=Elm 02 22 Base Level Engineering
Current Plan=p01
Default Exp/Contr=0.3,0.1
English Units
Geom File=g01
Flow File=f01
Plan File=p01
BEGIN DESCRIPTION:
Elm 02 22
END DESCRIPTION:

--- Elm 02 22.p01 (plan) ---

Plan Title=Multiple Run
Short Identifier=Multiple
Geom File=g01
Flow File=f01
Subcritical Flow
K Sum by GR= 0
Std Step Tol= 0.01
Critical Tol= 0.01
Num of Std Step Trials= 20
Max Error Tol= 0.3
Flow Tol Ratio= 0.001
Split Flow NTrial= 30
Split Flow Tol= 0.02
Split Flow Ratio= 0.02
Log Output Level= 0
Friction Slope Method= 1
Unsteady Friction Slope Method= 2
Unsteady Bridges Friction Slope Method= 1
Parabolic Critical Depth
Global Vel Dist=  1 , 1 , 1
Global Log Level= 0
CheckData=True
Encroach Param= -1, 0, 0, 0
BEGIN DESCRIPTION:
Multiple Run
END DESCRIPTION:

--- Elm 02 22.f01 (steady flow) ---

Flow Title=Multiple
Number of Profiles=7
Profile Names=10-year,25-year,50-year,1pct_min,100-year,1pct_plu,500-year
River Rch & RM= Elm 02 22,Reach-1,5151
     143     193     232     174     279     384     407
Boundary for River Rch & Prof#=Elm 02 22,Reach-1,1
Up Type=0
Dn Type=3
Dn Slope=0.001
Boundary for River Rch & Prof#=Elm 02 22,Reach-1,2
Up Type=0
Dn Type=3
Dn Slope=0.001
Boundary for River Rch & Prof#=Elm 02 22,Reach-1,3
Up Type=0
Dn Type=3
Dn Slope=0.001
Boundary for River Rch & Prof#=Elm 02 22,Reach-1,4
Up Type=0
Dn Type=3
Dn Slope=0.001
Boundary for River Rch & Prof#=Elm 02 22,Reach-1,5
Up Type=0
Dn Type=3
Dn Slope=0.001
Boundary for River Rch & Prof#=Elm 02 22,Reach-1,6
Up Type=0
Dn Type=3
Dn Slope=0.001
Boundary for River Rch & Prof#=Elm 02 22,Reach-1,7
Up Type=0
Dn Type=3
Dn Slope=0.001

--- Elm 02 22.g01 (geometry) ---

Geom Title=Existing Conditions

River Reach=Elm 02 22,Reach-1
Reach XY= 30
      1606555.00      6839138.00      1606562.75      6839244.22
      1606797.92      6839487.98      1606710.55      6839585.57
      1606656.10      6839748.55      1606705.49      6839998.17
      1606655.26      6840121.99      1606745.78      6840181.07
      1606713.04      6840237.98      1606747.25      6840287.91
      1606663.07      6840434.69      1606701.83      6840536.35
      1606604.61      6840658.13      1606660.37      6840890.70
      1606804.51      6840998.49      1606708.47      6841139.50
      1606706.96      6841232.11      1606847.14      6841381.83
      1606887.78      6841521.76      1607091.77      6841574.27
      1607155.60      6841767.95      1607057.24      6841993.93
      1607018.64      6842274.56      1606880.09      6842338.21
      1606670.16      6842337.34      1606601.68      6842296.04
      1606363.84      6842431.05      1606588.34      6842671.35
      1606691.75      6842724.22      1606655.00      6842788.00

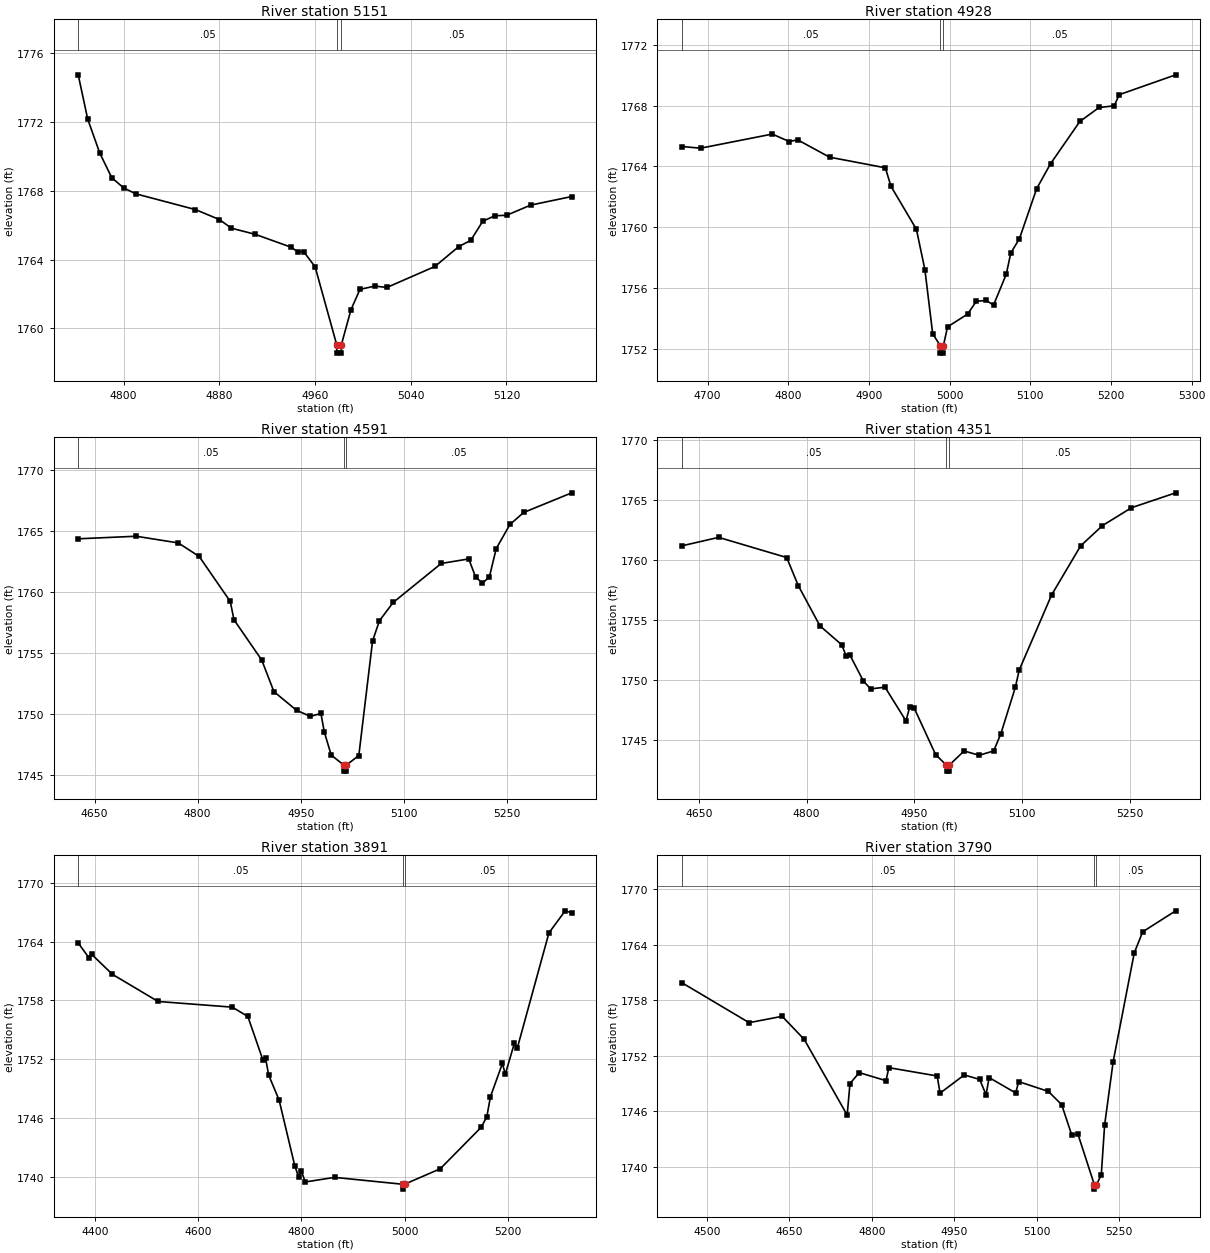
Type RM Length L Ch R = 1,5151,223,223,223
BEGIN DESCRIPTION:
Elm 02 22 4746.192
END DESCRIPTION:
XS GIS Cut Line= 3
      1606317.05      6839178.02      1606554.86      6839171.52
      1606729.41      6839167.17
#Sta/Elev= 30
  4762.1 1774.75  4770.0 1772.18  4780.1 1770.20  4790.1 1768.77  4800.1 1768.17
  4810.1 1767.83  4860.1 1766.91  4880.1 1766.33  4890.1 1765.83  4910.1 1765.47
  4940.1 1764.72  4945.5 1764.46  4950.5 1764.47  4960.1 1763.58  4978.1 1759.06
  4978.4 1758.56  4981.9 1758.56  4982.1 1759.06  4990.1 1761.09  4997.6 1762.27
  5010.1 1762.46  5020.1 1762.38  5060.2 1763.60  5080.2 1764.76  5090.2 1765.12
  5100.2 1766.23  5110.2 1766.55  5120.2 1766.58  5140.2 1767.17  5174.6 1767.67
#Mann=3,-1,0
  4762.1    0.05       0  4978.1    0.05       0  4982.1    0.05       0
Bank Sta=4978.1,4982.1
Exp/Cntr=0.3,0.1

Type RM Length L Ch R = 1,4928,337,337,337
BEGIN DESCRIPTION:
Elm 02 22 4928.07
END DESCRIPTION:
XS GIS Cut Line= 3
      1606338.75      6839460.15      1606653.46      6839358.14
      1606916.09      6839258.30
#Sta/Elev= 30
  4668.4 1765.30  4691.2 1765.19  4780.1 1766.12  4801.1 1765.63  4811.6 1765.74
  4851.1 1764.60  4920.3 1763.90  4927.3 1762.68  4958.8 1759.85  4969.3 1757.20
  4979.0 1752.97  4988.3 1752.20  4988.6 1751.70  4992.1 1751.70  4992.3 1752.20
  4997.4 1753.43  5022.3 1754.27  5033.0 1755.11  5045.4 1755.17  5054.4 1754.86
  5070.2 1756.90  5075.8 1758.29  5086.5 1759.23  5107.9 1762.53  5125.1 1764.17
  5161.4 1766.95  5185.3 1767.87  5204.1 1767.98  5210.1 1768.71  5280.2 1770.02
#Mann=3,-1,0
  4668.4    0.05       0  4988.3    0.05       0  4992.3    0.05       0
Bank Sta=4988.3,4992.3
Exp/Cntr=0.3,0.1

Type RM Length L Ch R = 1,4591,240,240,240
BEGIN DESCRIPTION:
Elm 02 22 4590.66
END DESCRIPTION:
XS GIS Cut Line= 3
      1606340.94      6839529.58      1606709.89      6839586.01
      1607054.94      6839583.84
#Sta/Elev= 30
  4626.2 1764.39  4710.6 1764.60  4771.9 1764.05  4802.3 1762.94  4847.5 1759.25
  4852.9 1757.75  4893.3 1754.45  4911.0 1751.86  4943.9 1750.33  4964.1 1749.83
  4979.4 1750.07  4984.5 1748.52  4994.4 1746.66  5012.6 1745.84  5012.8 1745.34
  5016.3 1745.34  5016.6 1745.84  5034.6 1746.62  5054.6 1756.01  5064.6 1757.67
  5084.6 1759.17  5154.6 1762.37  5194.6 1762.74  5204.6 1761.25  5214.6 1760.76
  5224.6 1761.26  5234.6 1763.59  5254.6 1765.57  5274.6 1766.55  5344.5 1768.16
#Mann=3,-1,0
  4626.2    0.05       0  5012.6    0.05       0  5016.6    0.05       0
Bank Sta=5012.6,5016.6
Exp/Cntr=0.3,0.1

Type RM Length L Ch R = 1,4351,460,460,460
BEGIN DESCRIPTION:
Elm 02 22 4350.6
END DESCRIPTION:
XS GIS Cut Line= 3
      1606284.50      6839766.12      1606653.46      6839809.53
      1606965.96      6839852.93
#Sta/Elev= 30
  4626.7 1761.15  4677.5 1761.85  4772.2 1760.17  4788.3 1757.84  4818.5 1754.48
  4848.7 1752.91  4855.2 1751.95  4860.3 1752.04  4878.9 1749.89  4889.0 1749.23
  4909.1 1749.37  4938.3 1746.56  4943.3 1747.69  4949.4 1747.67  4979.6 1743.75
  4994.5 1742.88  4994.7 1742.38  4998.2 1742.38  4998.5 1742.88  5019.2 1744.06
  5040.1 1743.70  5060.3 1744.06  5070.4 1745.50  5090.6 1749.38  5095.9 1750.80
  5141.1 1757.07  5181.5 1761.15  5211.8 1762.83  5252.2 1764.32  5313.7 1765.56
#Mann=3,-1,0
  4626.7    0.05       0  4994.5    0.05       0  4998.5    0.05       0
Bank Sta=4994.5,4998.5
Exp/Cntr=0.3,0.1

Type RM Length L Ch R = 1,3891,101,101,101
BEGIN DESCRIPTION:
Elm 02 22 3890.77
END DESCRIPTION:
XS GIS Cut Line= 4
      1606119.57      6840276.12      1606748.95      6840182.79
      1606840.09      6840126.37      1607035.42      6840039.56
#Sta/Elev= 30
  4367.0 1763.85  4387.9 1762.34  4393.0 1762.70  4433.1 1760.66  4521.8 1757.88
  4665.8 1757.30  4696.0 1756.35  4725.2 1751.90  4730.3 1752.10  4736.4 1750.36
  4756.6 1747.81  4787.0 1741.09  4794.7 1739.93  4799.7 1740.58  4807.2 1739.44
  4864.1 1739.91  4996.0 1739.21  4996.3 1738.71  5000.0 1739.21  5069.2 1740.79
  5148.8 1745.04  5159.6 1746.12  5166.5 1748.15  5189.8 1751.55  5195.3 1750.44
  5213.0 1753.63  5218.5 1753.10  5280.0 1764.89  5311.5 1767.14  5324.2 1766.93
#Mann=3,-1,0
  4367.0    0.05       0  4996.0    0.05       0  5000.0    0.05       0
Bank Sta=4996,5000
Exp/Cntr=0.3,0.1

Type RM Length L Ch R = 1,3790,110,110,110
BEGIN DESCRIPTION:
Elm 02 22 3789.97
END DESCRIPTION:
XS GIS Cut Line= 4
      1606193.35      6840332.54      1606529.76      6840310.83
      1606729.42      6840267.43      1607060.73      6840135.34
#Sta/Elev= 30
  4454.7 1759.89  4576.6 1755.58  4636.7 1756.27  4676.8 1753.77  4755.0 1745.58
  4760.1 1748.99  4777.0 1750.17  4825.7 1749.30  4830.8 1750.71  4918.8 1749.81
  4924.0 1747.95  4968.0 1749.92  4996.1 1749.44  5007.8 1747.77  5013.2 1749.64
  5061.7 1747.97  5067.1 1749.20  5121.0 1748.14  5145.3 1746.71  5163.6 1743.43
  5174.9 1743.52  5204.7 1738.06  5204.9 1737.56  5208.7 1738.06  5217.4 1739.09
  5223.5 1744.50  5239.0 1751.35  5277.4 1763.13  5292.8 1765.42  5352.8 1767.69
#Mann=3,-1,0
  4454.7    0.05       0  5204.7    0.05       0  5208.7    0.05       0
Bank Sta=5204.7,5208.7
Exp/Cntr=0.3,0.1

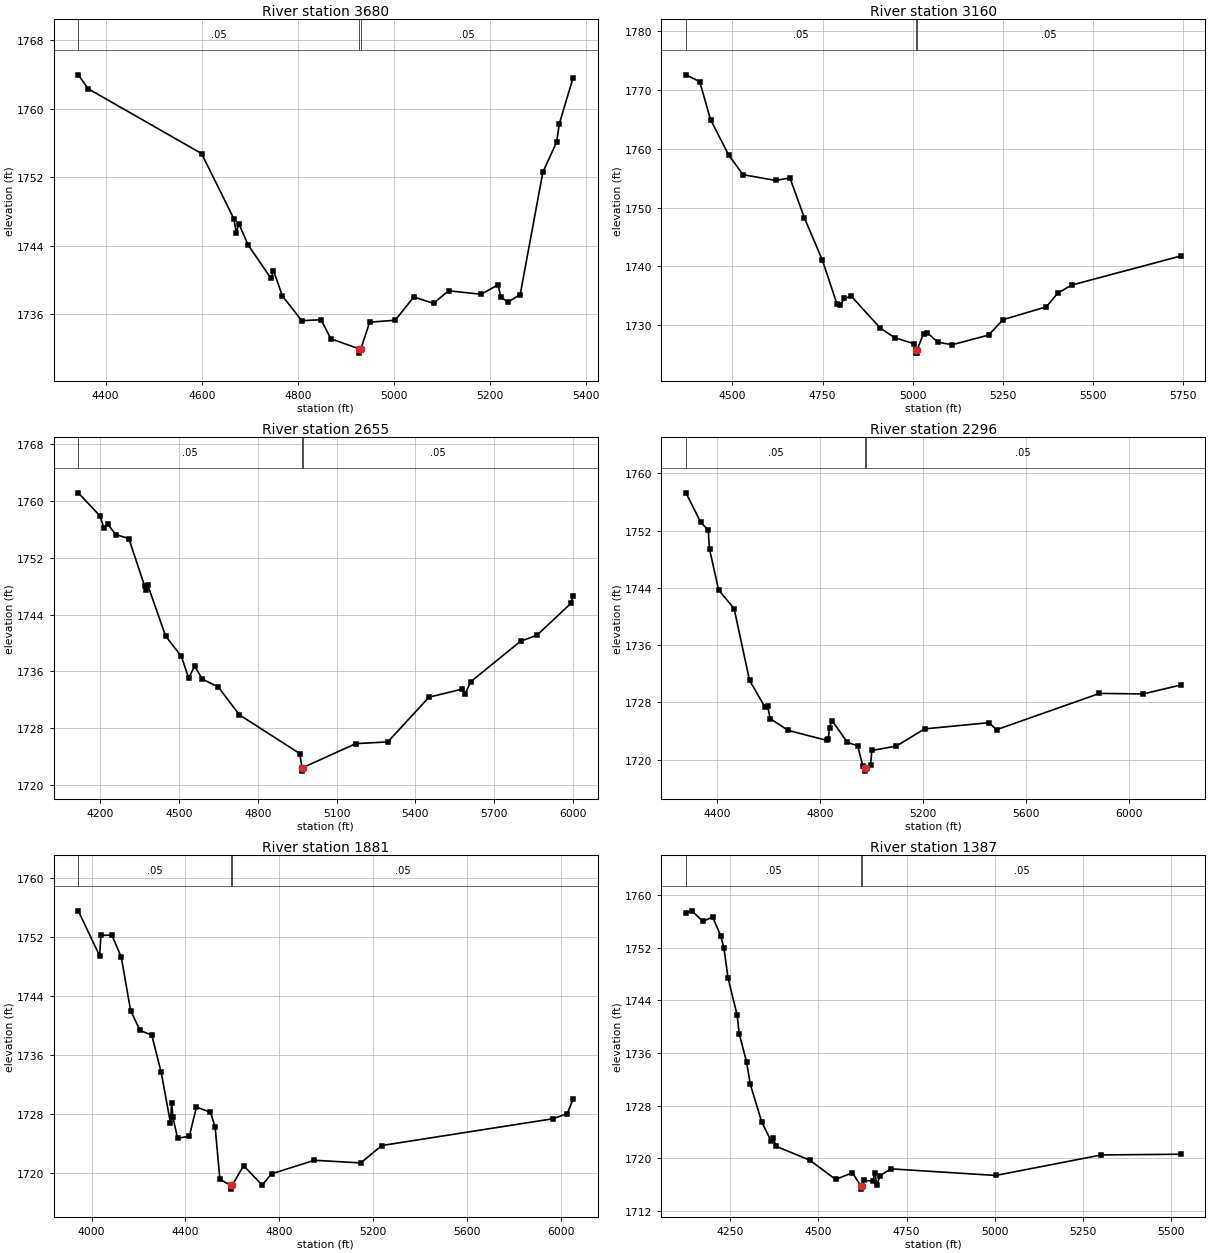
Type RM Length L Ch R = 1,3680,520,520,520
BEGIN DESCRIPTION:
Elm 02 22 3679.67
END DESCRIPTION:
XS GIS Cut Line= 3
      1606054.51      6840447.55      1606705.55      6840358.58
      1607065.77      6840265.26
#Sta/Elev= 30
  4343.1 1763.94  4363.8 1762.31  4599.6 1754.75  4666.6 1747.16  4671.9 1745.50
  4676.9 1746.58  4696.8 1744.05  4744.1 1740.18  4749.2 1741.10  4767.5 1738.15
  4807.9 1735.25  4848.2 1735.35  4868.4 1733.14  4927.0 1731.96  4927.2 1731.46
  4931.0 1731.96  4949.2 1735.07  5002.5 1735.30  5040.9 1738.01  5082.3 1737.27
  5113.3 1738.74  5181.2 1738.33  5216.6 1739.44  5221.8 1738.01  5237.2 1737.42
  5262.4 1738.30  5309.5 1752.57  5338.4 1756.13  5343.6 1758.20  5372.3 1763.58
#Mann=3,-1,0
  4343.1    0.05       0  4927.0    0.05       0  4931.0    0.05       0
Bank Sta=4927,4931
Exp/Cntr=0.3,0.1

Type RM Length L Ch R = 1,3160,505,505,505
BEGIN DESCRIPTION:
Elm 02 22 3160.05
END DESCRIPTION:
XS GIS Cut Line= 3
      1606026.87      6840776.76      1606658.37      6840798.46
      1607396.25      6840750.72
#Sta/Elev= 30
  4371.3 1772.61  4409.5 1771.46  4439.5 1764.99  4489.5 1758.99  4529.5 1755.61
  4619.6 1754.63  4659.6 1755.05  4699.6 1748.27  4749.7 1741.03  4789.7 1733.63
  4799.7 1733.36  4809.7 1734.55  4829.7 1734.92  4909.7 1729.51  4949.8 1727.87
  5003.2 1726.83  5007.8 1725.73  5008.1 1725.23  5011.6 1725.23  5011.8 1725.73
  5029.9 1728.57  5039.9 1728.72  5069.9 1727.07  5110.0 1726.67  5210.2 1728.30
  5250.3 1730.93  5370.6 1733.12  5401.6 1735.44  5440.7 1736.82  5742.6 1741.76
#Mann=3,-1,0
  4371.3    0.05       0  5007.8    0.05       0  5011.8    0.05       0
Bank Sta=5007.8,5011.8
Exp/Cntr=0.3,0.1

Type RM Length L Ch R = 1,2655,359,359,359
BEGIN DESCRIPTION:
Elm 02 22 2654.93
END DESCRIPTION:
XS GIS Cut Line= 3
      1605822.89      6841239.00      1606703.94      6841184.75
      1607620.98      6840781.51
#Sta/Elev= 30
  4116.4 1761.14  4198.7 1757.90  4213.8 1756.24  4228.7 1756.76  4258.8 1755.27
  4308.9 1754.71  4369.0 1748.04  4375.4 1747.45  4380.4 1748.21  4449.1 1740.99
  4509.3 1738.11  4536.9 1735.06  4559.3 1736.76  4589.4 1734.92  4649.5 1733.83
  4729.7 1729.91  4960.1 1724.45  4968.1 1722.48  4968.4 1721.98  4972.1 1722.48
  5173.5 1725.85  5295.2 1726.09  5452.1 1732.38  5579.8 1733.53  5590.2 1732.89
  5612.0 1734.59  5800.8 1740.25  5863.3 1741.10  5993.0 1745.59  6000.9 1746.63
#Mann=3,-1,0
  4116.4    0.05       0  4968.1    0.05       0  4972.1    0.05       0
Bank Sta=4968.1,4972.1
Exp/Cntr=0.3,0.1

Type RM Length L Ch R = 1,2296,415,415,415
BEGIN DESCRIPTION:
Elm 02 22 2295.98
END DESCRIPTION:
XS GIS Cut Line= 3
      1606137.84      6841516.94      1606860.08      6841485.69
      1608060.74      6841478.75
#Sta/Elev= 30
  4278.3 1757.27  4335.5 1753.17  4365.0 1752.06  4370.0 1749.39  4405.6 1743.69
  4465.6 1741.09  4525.7 1731.06  4585.7 1727.33  4595.8 1727.49  4605.8 1725.73
  4675.8 1724.07  4826.0 1722.68  4831.6 1722.83  4836.6 1724.44  4846.0 1725.45
  4906.0 1722.41  4946.1 1721.91  4966.1 1719.09  4974.1 1718.88  4974.4 1718.38
  4978.1 1718.88  4996.1 1719.19  5001.2 1721.27  5096.1 1721.87  5206.1 1724.28
  5456.1 1725.15  5486.1 1724.17  5886.2 1729.24  6056.2 1729.17  6201.9 1730.41
#Mann=3,-1,0
  4278.3    0.05       0  4974.1    0.05       0  4978.1    0.05       0
Bank Sta=4974.1,4978.1
Exp/Cntr=0.3,0.1

Type RM Length L Ch R = 1,1881,494,494,494
BEGIN DESCRIPTION:
Elm 02 22 1881.31
END DESCRIPTION:
XS GIS Cut Line= 3
      1606071.90      6841746.11      1607123.97      6841711.39
      1608179.54      6841725.27
#Sta/Elev= 30
  3943.3 1755.54  4034.5 1749.42  4039.5 1752.21  4086.5 1752.25  4126.5 1749.26
  4166.5 1742.01  4206.5 1739.34  4256.6 1738.69  4296.6 1733.66  4336.1 1726.81
  4341.1 1729.57  4346.6 1727.56  4366.6 1724.72  4416.7 1725.01  4446.7 1728.95
  4506.7 1728.25  4526.7 1726.20  4546.7 1719.16  4594.8 1718.34  4595.0 1717.84
  4598.8 1718.34  4647.8 1721.01  4726.8 1718.38  4766.8 1719.91  4949.5 1721.75
  5147.0 1721.39  5237.0 1723.75  5967.1 1727.38  6027.1 1728.08  6051.6 1730.01
#Mann=3,-1,0
  3943.3    0.05       0  4594.8    0.03       0  4598.8    0.05       0
Bank Sta=4594.8,4598.8
Exp/Cntr=0.3,0.1

Type RM Length L Ch R = 1,1387,727,727,727
BEGIN DESCRIPTION:
Elm 02 22 1386.91
END DESCRIPTION:
XS GIS Cut Line= 3
      1606221.18      6841898.88      1607054.53      6842166.25
      1607578.79      6842214.85
#Sta/Elev= 30
  4124.7 1757.34  4141.3 1757.62  4173.4 1756.00  4200.3 1756.70  4223.2 1753.85
  4232.4 1751.94  4244.2 1747.36  4269.8 1741.77  4275.7 1738.89  4296.7 1734.61
  4307.2 1731.21  4339.3 1725.53  4366.2 1722.58  4371.4 1723.09  4380.8 1721.79
  4475.3 1719.70  4548.8 1716.77  4596.3 1717.77  4620.3 1715.79  4620.6 1715.29
  4624.3 1715.79  4628.4 1716.63  4653.8 1716.51  4660.5 1717.75  4665.7 1715.91
  4674.8 1717.36  4706.3 1718.37  5002.6 1717.37  5301.6 1720.49  5526.4 1720.60
#Mann=3,-1,0
  4124.7    0.05       0  4620.3    0.05       0  4624.3    0.05       0
Bank Sta=4620.3,4624.3
Exp/Cntr=0.3,0.1

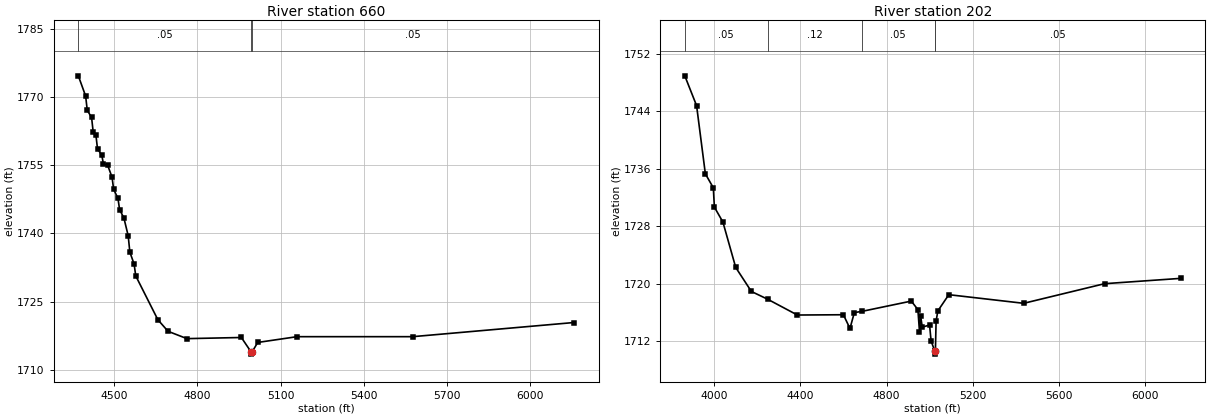
Type RM Length L Ch R = 1,660,458,458,458
BEGIN DESCRIPTION:
Elm 02 22 659.56
END DESCRIPTION:
XS GIS Cut Line= 4
      1605929.50      6842048.17      1606471.19      6842374.58
      1606981.61      6842454.44      1607596.23      6842284.29
#Sta/Elev= 30
  4371.1 1774.68  4397.4 1770.23  4403.3 1767.08  4418.8 1765.54  4424.6 1762.34
  4434.3 1761.71  4440.2 1758.63  4455.7 1757.19  4461.5 1755.29  4477.0 1754.96
  4492.6 1752.37  4498.4 1749.69  4513.9 1747.71  4519.8 1745.25  4535.3 1743.39
  4550.8 1739.48  4556.7 1735.90  4572.2 1733.23  4578.0 1730.65  4657.7 1721.00
  4694.5 1718.45  4762.5 1716.84  4958.6 1717.09  4993.5 1713.93  4993.7 1713.43
  4997.5 1713.93  5017.5 1716.00  5159.2 1717.27  5575.6 1717.27  6157.9 1720.39
#Mann=3,-1,0
  4371.1    0.05       0  4993.5    0.05       0  4997.5    0.05       0
Bank Sta=4993.5,4997.5
Exp/Cntr=0.3,0.1

Type RM Length L Ch R = 1,202,0,0,0
BEGIN DESCRIPTION:
Elm 02 22 535.271
END DESCRIPTION:
XS GIS Cut Line= 3
      1605471.15      6842457.91      1606588.34      6842671.35
      1607699.53      6842316.41
#Sta/Elev= 30
  3862.6 1748.93  3917.4 1744.78  3958.1 1735.30  3995.1 1733.35  4000.1 1730.66
  4039.6 1728.59  4099.2 1722.27  4171.9 1718.93  4248.1 1717.84  4385.7 1715.65
  4599.5 1715.69  4630.1 1713.78  4650.4 1715.99  4684.3 1716.15  4915.1 1717.59
  4945.7 1716.40  4953.1 1713.34  4958.2 1715.54  4966.1 1713.96  5000.0 1714.26
  5007.0 1712.05  5023.1 1710.71  5023.3 1710.21  5027.1 1710.71  5030.3 1714.81
  5038.5 1716.23  5089.4 1718.48  5437.4 1717.28  5813.1 1720.01  6166.5 1720.75
#Mann=5,-1,0
  3862.6    0.05       0  4248.1    0.12       0  4684.3    0.05       0
  5023.1    0.05       0  5027.1    0.05       0
Bank Sta=5023.1,5027.1
Exp/Cntr=0.3,0.1

Chan Stop Cuts=-1