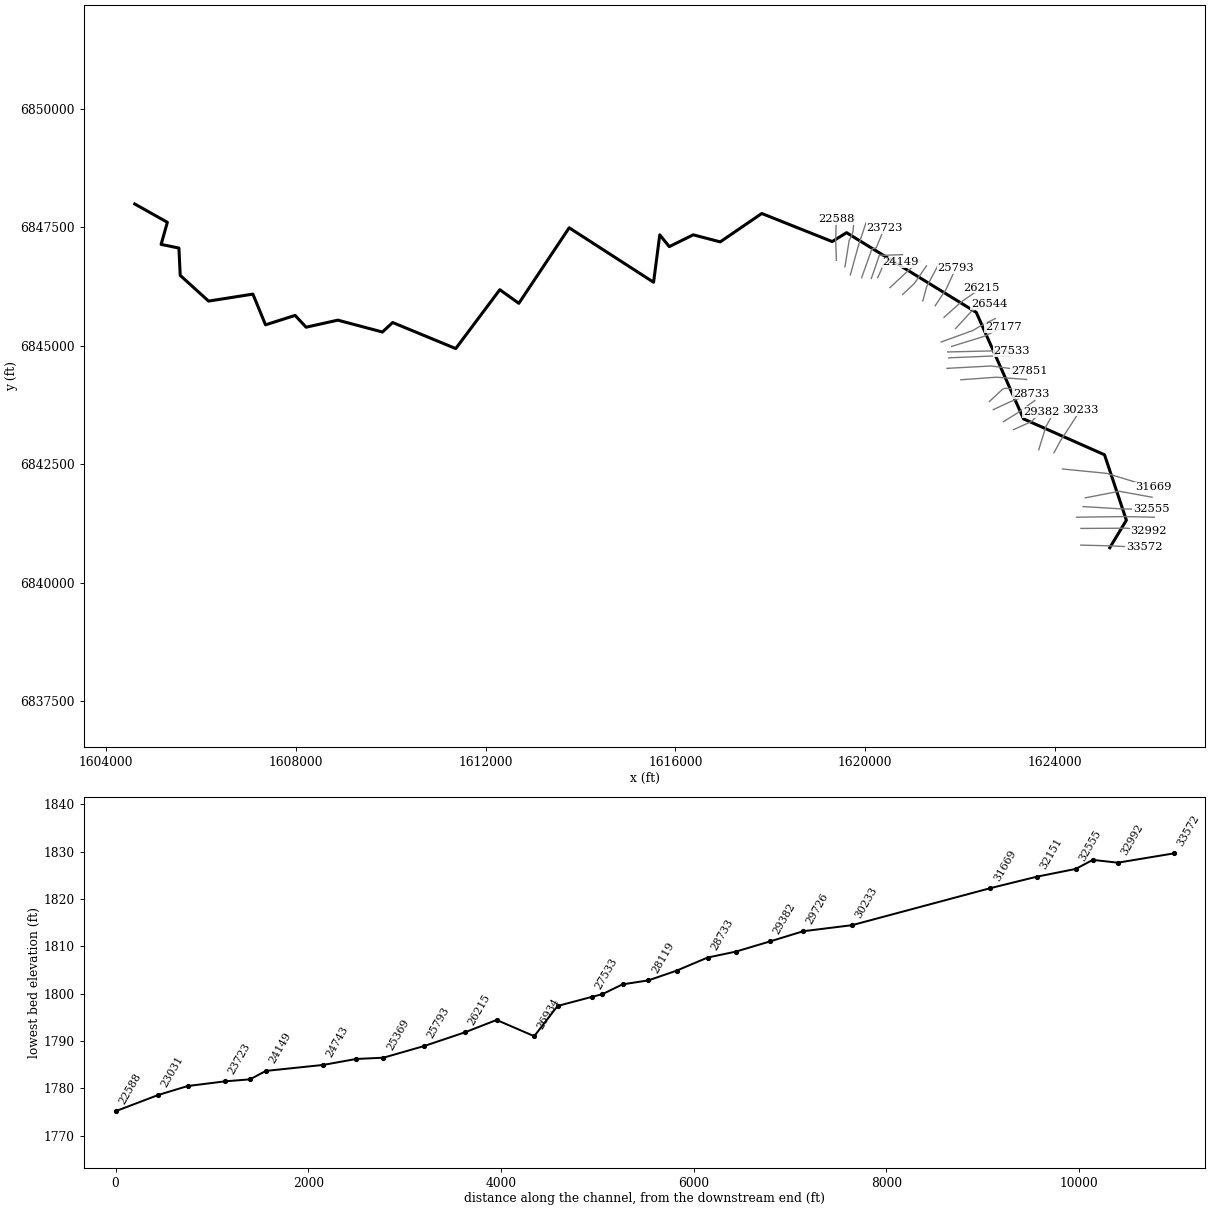
--- Elm 02 23.prj (project) ---

Proj Title=Elm 02 23 Base Level Engineering
Current Plan=p01
Default Exp/Contr=0.3,0.1
English Units
Geom File=g01
Flow File=f01
Plan File=p01
Y Axis Title=Elevation
X Axis Title(PF)=Main Channel Distance
X Axis Title(XS)=Station
BEGIN DESCRIPTION:
Elm 02 23
END DESCRIPTION:
DSS Export Rating Curves= 0
DSS Export Rating Curve Sorted= 0
DSS Export Volume Flow Curves= 0
DXF OffsetX= 0
DXF OffsetY= 0
DXF ScaleX= 1
DXF ScaleY= 10

--- Elm 02 23.p01 (plan) ---

Plan Title=Multiple Run
Short Identifier=Multiple
Geom File=g01
Flow File=f01
Subcritical Flow
K Sum by GR= 0
Std Step Tol= 0.01
Critical Tol= 0.01
Num of Std Step Trials= 20
Max Error Tol= 0.3
Flow Tol Ratio= 0.001
Split Flow NTrial= 30
Split Flow Tol= 0.02
Split Flow Ratio= 0.02
Log Output Level= 0
Friction Slope Method= 1
Unsteady Friction Slope Method= 2
Unsteady Bridges Friction Slope Method= 1
Parabolic Critical Depth
Global Vel Dist=  1 , 1 , 1
Global Log Level= 0
CheckData=True
Encroach Param= -1, 0, 0, 0
BEGIN DESCRIPTION:
Multiple Run
END DESCRIPTION:

--- Elm 02 23.f01 (steady flow) ---

Flow Title=Multiple
Number of Profiles=7
Profile Names=10-year,25-year,50-year,1pct_min,100-year,1pct_plu,500-year
River Rch & RM= Elm 02 23,Reach-1,33572
     204     279     340     257     411     566     612
River Rch & RM= Elm 02 23,Reach-1,31669
     264     365     449     342     547     753     826
River Rch & RM= Elm 02 23,Reach-1,27177
     367     518     644     496     795    1090    1230
River Rch & RM= Elm 02 23,Reach-1,24743
     447     636     795     616     987    1360    1540
River Rch & RM= Elm 02 23,Reach-1,16781
     573     823    1040     807    1290    1780    2040
River Rch & RM= Elm 02 23,Reach-1,10737
     640     922    1160     907    1450    2000    2300
River Rch & RM= Elm 02 23,Reach-1,3046
     690     997    1260     984    1580    2170    2500
Boundary for River Rch & Prof#=Elm 02 23,Reach-1,1
Up Type=0
Dn Type=3
Dn Slope=0.001
Boundary for River Rch & Prof#=Elm 02 23,Reach-1,2
Up Type=0
Dn Type=3
Dn Slope=0.001
Boundary for River Rch & Prof#=Elm 02 23,Reach-1,3
Up Type=0
Dn Type=3
Dn Slope=0.001
Boundary for River Rch & Prof#=Elm 02 23,Reach-1,4
Up Type=0
Dn Type=3
Dn Slope=0.001
Boundary for River Rch & Prof#=Elm 02 23,Reach-1,5
Up Type=0
Dn Type=3
Dn Slope=0.001
Boundary for River Rch & Prof#=Elm 02 23,Reach-1,6
Up Type=0
Dn Type=3
Dn Slope=0.001
Boundary for River Rch & Prof#=Elm 02 23,Reach-1,7
Up Type=0
Dn Type=3
Dn Slope=0.001

--- Elm 02 23.g01 (geometry) ---

Geom Title=Existing Conditions
Program Version=4.10

River Reach=Elm 02 23       ,Reach-1
Reach XY= 30
        1625155.        6840738.      1625504.94      6841317.97
      1625044.68      6842698.18      1623338.25      6843454.46
      1622341.63      6845701.32      1619607.28      6847382.95
       1619304.9      6847195.31      1617820.21      6847787.49
      1616944.57      6847189.03       1616375.3      6847337.73
      1615870.34      6847088.18      1615670.42      6847338.14
      1615539.91      6846337.28      1613760.89      6847486.04
      1612699.89      6845892.95      1612298.83      6846180.24
      1611370.22      6844938.51      1610039.64      6845488.11
      1609825.23      6845287.51      1608884.97      6845537.93
      1608215.53      6845389.08      1607985.05      6845638.26
      1607360.83      6845439.53      1607094.45       6846086.9
      1606160.86      6845940.07       1605562.8      6846481.79
      1605535.42      6847058.59      1605160.06       6847135.7
      1605291.77      6847601.73        1604605.        6847988.

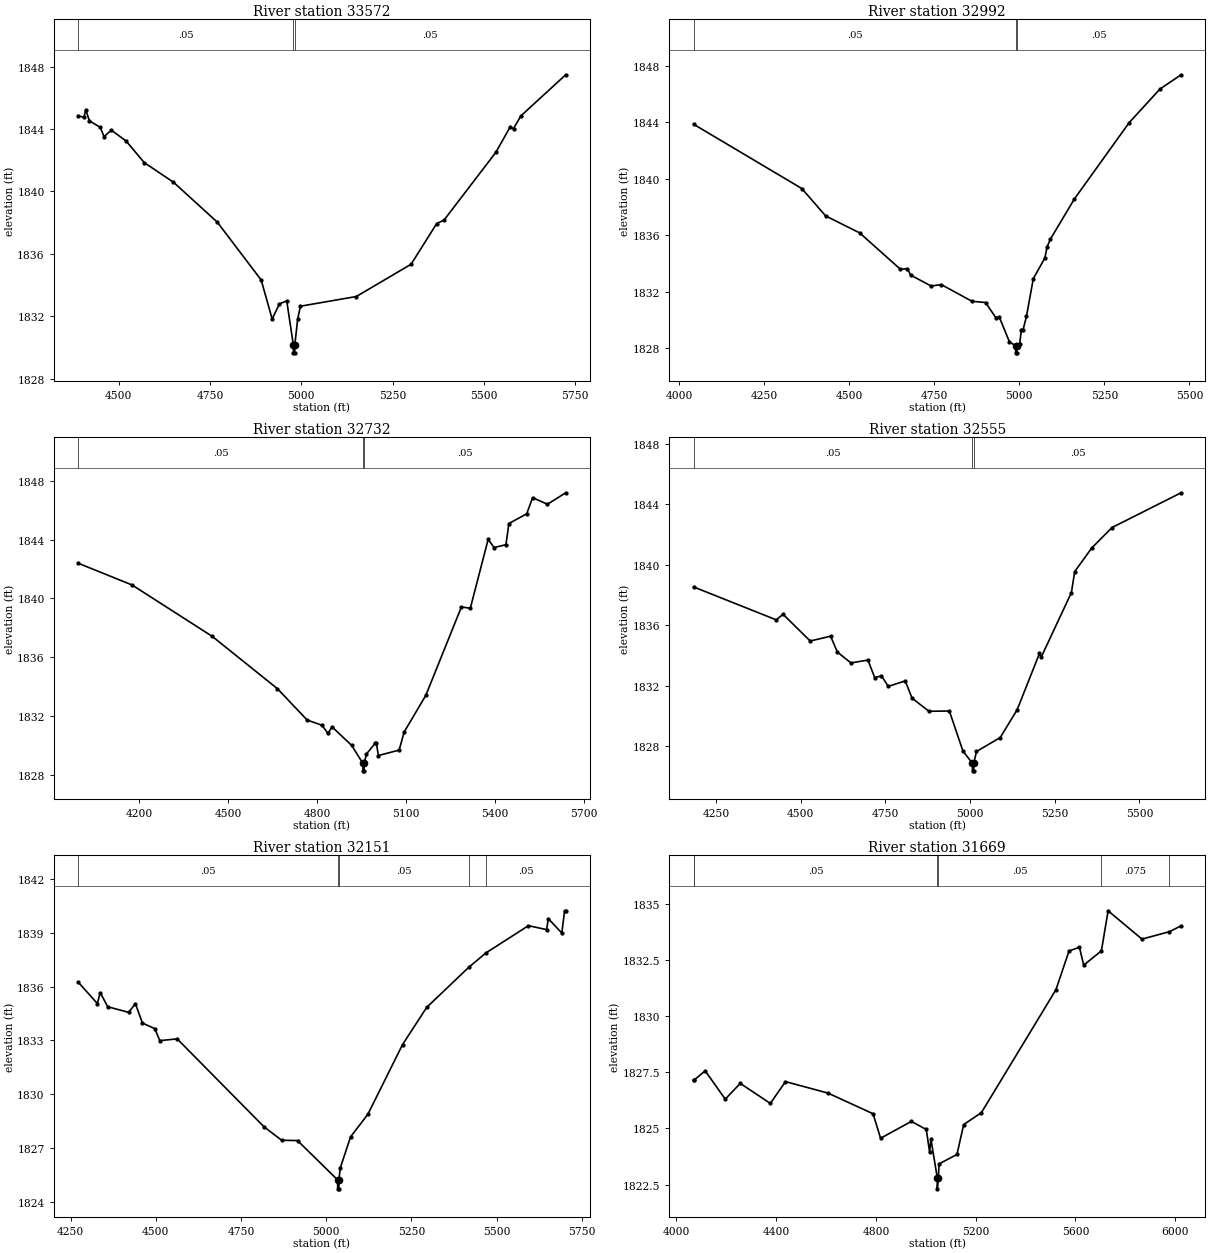
Type RM Length L Ch R = 1 ,33572   ,580,580,580
BEGIN DESCRIPTION:
Elm 02 23 33391.642
END DESCRIPTION:
XS GIS Cut Line= 3
      1624544.38      6840793.39      1625154.68      6840777.77
      1625877.69      6840743.91
#Sta/Elev= 30
  4389.5 1844.85  4404.9 1844.75  4410.1 1845.23  4420.1 1844.53  4450.1  1844.1
  4460.1 1843.51  4480.1 1843.93  4520.2 1843.24  4570.2 1841.85  4650.2 1840.59
  4770.2 1838.03  4890.3 1834.32  4920.3 1831.82  4940.3 1832.79  4960.3 1832.98
  4978.3 1830.15  4978.6 1829.65  4982.1 1829.65  4982.3 1830.15  4990.3 1831.84
  4997.7 1832.64  5150.5 1833.26  5300.6 1835.33  5370.7 1837.94  5390.7 1838.16
  5532.7 1842.51  5570.9  1844.1    5581 1844.03    5601 1844.84  5723.8 1847.48
#Mann= 3 ,-1 , 0
  4389.5     .05       0  4978.3     .03       0  4982.3     .05       0
Bank Sta=4978.3,4982.3
XS Rating Curve= 0 ,0
Exp/Cntr=0.3,0.1

Type RM Length L Ch R = 1 ,32992   ,260,260,260
BEGIN DESCRIPTION:
Elm 02 23 32991.6
END DESCRIPTION:
XS GIS Cut Line= 3
      1624546.99      6841144.95      1625510.51      6841150.16
      1625976.66      6841100.68
#Sta/Elev= 30
  4042.9 1843.87  4360.9 1839.32  4430.9 1837.38  4530.9 1836.18  4650.9  1833.6
  4670.9 1833.65  4680.9 1833.19  4740.9 1832.42  4770.9 1832.52  4860.9 1831.34
  4900.9 1831.25  4930.9 1830.18  4940.9 1830.24  4970.9 1828.47  4988.9 1828.19
  4989.2 1827.69  4992.7 1827.69  4992.9 1828.19  5000.9  1828.3  5006.2 1829.34
  5011.2 1829.34    5021 1830.27  5041.1 1832.94  5075.3 1834.41  5081.3 1835.17
  5091.4 1835.74  5161.8 1838.58  5322.7 1843.98  5413.2 1846.36  5475.2 1847.37
#Mann= 3 ,-1 , 0
  4042.9     .05       0  4988.9     .03       0  4992.9     .05       0
Bank Sta=4988.9,4992.9
XS Rating Curve= 0 ,0
Exp/Cntr=0.3,0.1

Type RM Length L Ch R = 1 ,32732   ,177,177,177
BEGIN DESCRIPTION:
Elm 02 23 32731.74
END DESCRIPTION:
XS GIS Cut Line= 3
      1624453.21      6841381.93      1625458.43      6841394.95
      1626096.49      6841381.93
#Sta/Elev= 30
    3995 1842.39  4176.8 1840.91  4446.8 1837.42  4666.8 1833.86  4766.9 1831.73
  4816.9 1831.38  4836.9 1830.82  4850.7 1831.27  4916.9 1830.01  4954.9 1828.78
  4955.1 1828.28  4958.6 1828.28  4958.9 1828.78  4966.9 1829.43  4996.1 1830.15
  5000.3 1830.15  5006.9 1829.32  5076.9 1829.69  5093.9 1830.92  5166.9 1833.41
  5286.9 1839.42  5316.9 1839.33    5377 1844.01    5397 1843.46    5437 1843.65
    5447 1845.09    5507 1845.75    5527 1846.85    5577  1846.4  5638.5 1847.18
#Mann= 3 ,-1 , 0
    3995     .05       0  4954.9     .05       0  4958.9     .05       0
Bank Sta=4954.9,4958.9
XS Rating Curve= 0 ,0
Exp/Cntr=0.3,0.1

Type RM Length L Ch R = 1 ,32555   ,404,404,404
BEGIN DESCRIPTION:
Elm 02 23 32554.55
END DESCRIPTION:
XS GIS Cut Line= 3
      1624591.27      6841605.89      1625408.95      6841556.41
      1626028.79      6841545.99
#Sta/Elev= 30
  4183.7 1838.54  4427.9 1836.36  4447.9 1836.73  4528.1 1834.96  4588.2 1835.28
  4608.2 1834.23  4648.3 1833.51  4698.4  1833.7  4718.4 1832.54  4738.4 1832.65
  4758.5 1831.96  4808.6 1832.32  4828.6 1831.18  4878.7 1830.31  4938.8 1830.33
  4978.9 1827.68  5006.9 1826.87  5007.2 1826.37  5010.7 1826.37  5010.9 1826.87
  5018.9 1827.65  5088.9 1828.57  5138.9 1830.41  5204.9 1834.14  5209.9 1833.89
    5299 1838.16    5309 1839.56    5359 1841.11    5419 1842.47  5622.8 1844.77
#Mann= 3 ,-1 , 0
  4183.7     .05       0  5006.9     .05       0  5010.9     .05       0
Bank Sta=5006.9,5010.9
XS Rating Curve= 0 ,0
Exp/Cntr=0.3,0.1

Type RM Length L Ch R = 1 ,32151   ,482,482,482
BEGIN DESCRIPTION:
Elm 02 23 32151.2
END DESCRIPTION:
XS GIS Cut Line= 3
      1624639.94      6841790.09      1625356.11      6841928.99
      1626046.21      6841803.12
#Sta/Elev= 30
  4272.1 1836.25  4328.2 1835.06  4336.6 1835.67  4358.7 1834.88  4419.9 1834.57
    4440 1835.05  4460.6 1833.97  4496.9 1833.66  4511.5 1832.99  4562.5 1833.09
  4817.4 1828.19  4869.1 1827.44  4915.8 1827.42  5033.5 1825.23  5033.8 1824.73
  5037.3 1824.73  5037.5 1825.23  5041.1 1825.88  5071.6 1827.63  5122.5 1828.89
  5224.1 1832.77  5295.3 1834.85  5418.6 1837.08  5468.9 1837.88  5593.7  1839.4
    5647 1839.18  5652.1 1839.79  5691.7 1838.99  5699.9 1840.23  5703.1 1840.23
#Mann= 5 ,-1 , 0
  4272.1     .05       0  5033.5     .03       0  5037.5     .05       0
  5418.6    .075       0  5468.9     .05       0
Bank Sta=5033.5,5037.5
XS Rating Curve= 0 ,0
Exp/Cntr=0.3,0.1

Type RM Length L Ch R = 1 ,31669   ,1436,1436,1436
BEGIN DESCRIPTION:
Elm 02 23 31669.08
END DESCRIPTION:
XS GIS Cut Line= 3
      1624158.66      6842398.89      1625087.44      6842306.88
      1626064.92      6842009.99
#Sta/Elev= 30
  4068.8 1827.16    4072 1827.16  4115.4 1827.56  4195.8  1826.3  4256.1    1827
  4376.6 1826.11  4437.4 1827.08  4607.8 1826.57  4788.6 1825.65  4818.8 1824.56
  4942.2 1825.31  5002.1 1824.95  5015.4 1823.94  5020.6 1824.53    5046 1822.81
  5046.3 1822.31  5050.4 1822.81  5053.5 1823.42    5125 1823.84  5152.1 1825.17
  5223.1  1825.7  5522.1 1831.17  5574.4 1832.89  5616.2 1833.06  5633.4 1832.26
  5704.4  1832.9  5731.2 1834.68    5867 1833.42  5977.2 1833.75  6023.7 1834.01
#Mann= 6 ,-1 , 0
  4068.8    .075       0    4072     .05       0    5046     .05       0
  5050.4     .05       0  5704.4    .075       0  5977.2     .05       0
Bank Sta=5046,5050.4
XS Rating Curve= 0 ,0
Exp/Cntr=0.3,0.1

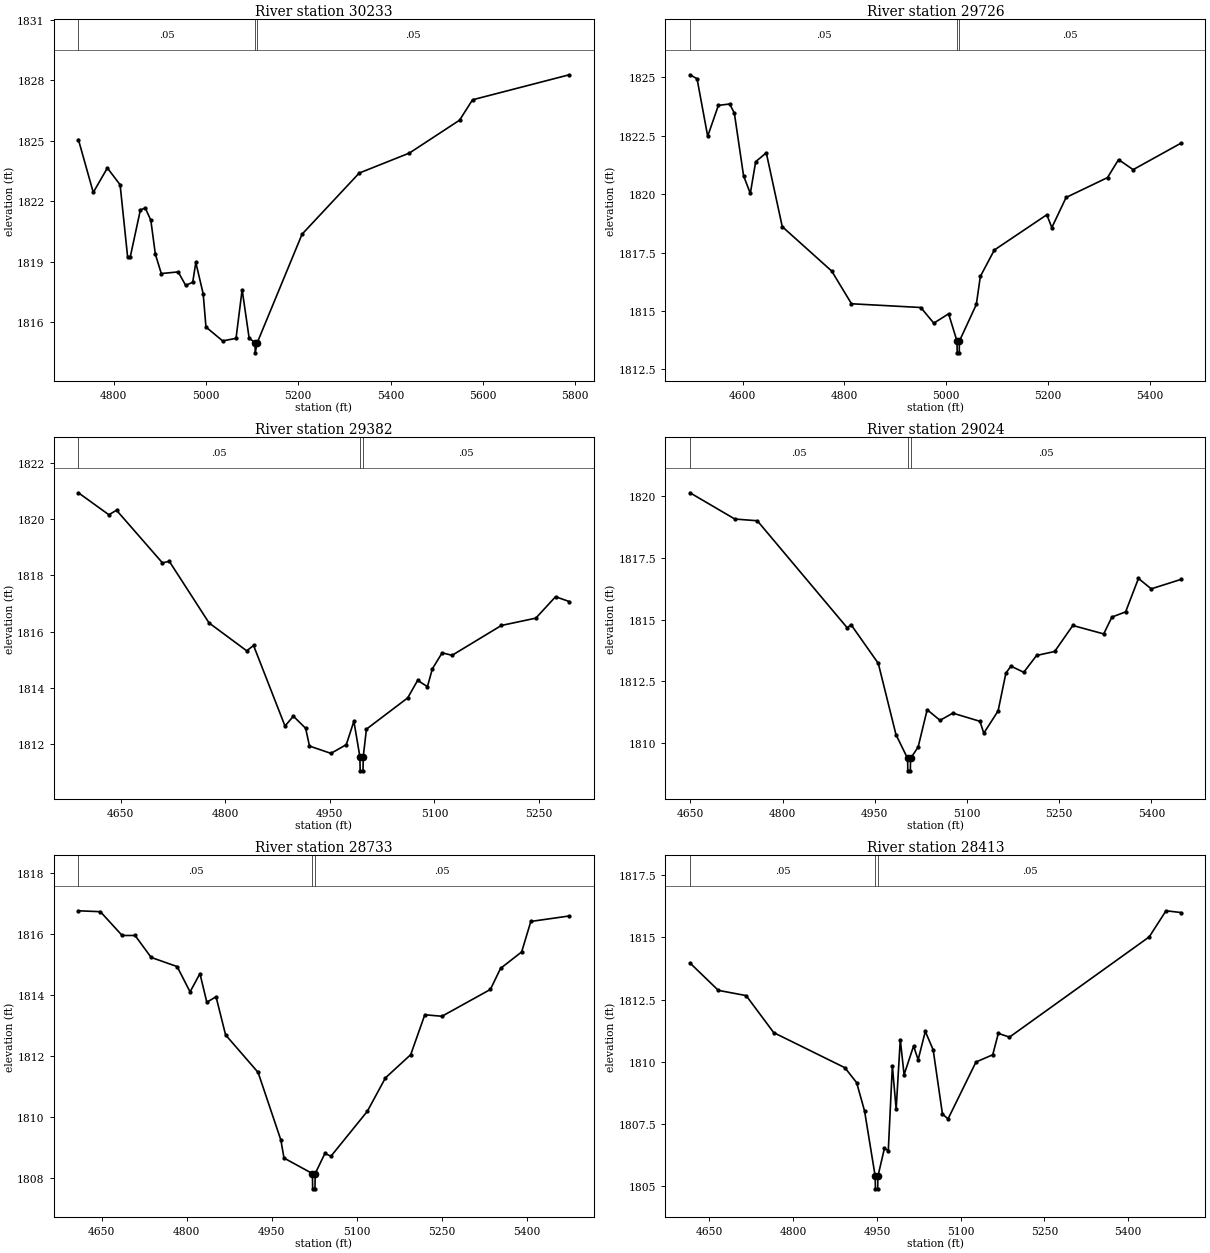
Type RM Length L Ch R = 1 ,30233   ,507,507,507
BEGIN DESCRIPTION:
Elm 02 23 30232.99
END DESCRIPTION:
XS GIS Cut Line= 3
      1623979.23      6842739.62      1624110.43      6842984.34
      1624538.65      6843643.84
#Sta/Elev= 30
  4723.4 1825.06  4755.6 1822.44  4786.2 1823.65  4813.8 1822.82  4830.1 1819.24
  4835.8 1819.24  4857.7 1821.57  4868.3 1821.67  4880.4 1821.06  4890.2 1819.38
  4903.1 1818.42  4939.7  1818.5    4956 1817.83  4971.2 1817.99  4977.9 1818.97
  4993.9 1817.41  4999.9 1815.77  5036.1 1815.08  5065.1 1815.21  5078.3 1817.62
  5093.5 1815.22  5106.3 1814.99  5106.6 1814.49    5111 1814.99  5208.2 1820.37
  5332.1  1823.4  5440.8 1824.39  5549.6 1826.02  5577.7 1827.03  5787.4 1828.27
#Mann= 3 ,-1 , 0
  4723.4     .05       0  5106.3     .03       0    5111     .05       0
Bank Sta=5106.3,5111
XS Rating Curve= 0 ,0
Exp/Cntr=0.3,0.1

Type RM Length L Ch R = 1 ,29726   ,344,344,344
BEGIN DESCRIPTION:
Elm 02 23 29727.41
END DESCRIPTION:
XS GIS Cut Line= 3
      1623658.06      6842804.74      1623808.78      6843290.33
      1624029.16      6843690.18
#Sta/Elev= 30
  4496.5 1825.11  4510.4 1824.94  4531.3 1822.48  4552.3  1823.8  4574.5 1823.86
  4583.7 1823.47  4601.8 1820.79  4615.1 1820.03  4625.6 1821.39  4646.5 1821.77
  4677.9 1818.61  4775.1 1816.71    4814 1815.31  4950.2 1815.15  4975.8 1814.48
  5004.9 1814.88  5021.4 1813.71  5021.8 1813.21  5025.8 1813.21  5026.1 1813.71
  5059.4 1815.28  5067.3 1816.48  5094.8 1817.61    5198 1819.12  5207.8 1818.57
  5235.9 1819.86  5317.3 1820.71    5339 1821.48  5367.7 1821.05  5461.5 1822.18
#Mann= 3 ,-1 , 0
  4496.5     .05       0  5021.4     .05       0  5026.1     .05       0
Bank Sta=5021.4,5026.1
XS Rating Curve= 0 ,0
Exp/Cntr=0.3,0.1

Type RM Length L Ch R = 1 ,29382   ,358,358,358
BEGIN DESCRIPTION:
Elm 02 23 29381.64
END DESCRIPTION:
XS GIS Cut Line= 3
      1623125.21       6843227.4      1623502.79      6843398.84
      1623710.59      6843600.14
#Sta/Elev= 30
  4589.4 1820.93  4633.1 1820.15  4644.1 1820.31    4710 1818.44  4719.7  1818.5
  4776.8 1816.31  4830.8 1815.32  4840.6 1815.51  4885.7 1812.65  4897.7    1813
  4915.3 1812.57  4920.8 1811.94  4951.6 1811.68  4973.6 1811.99  4984.5 1812.82
  4993.1 1811.56  4993.5 1811.06  4997.6 1811.06  4997.9 1811.56  5002.5 1812.54
  5061.7 1813.65  5075.9 1814.27    5090 1814.05    5097 1814.68  5111.1 1815.25
  5125.3 1815.16    5196 1816.22  5245.4 1816.48  5273.7 1817.24  5293.4 1817.07
#Mann= 3 ,-1 , 0
  4589.4     .05       0  4993.1     .05       0  4997.9     .05       0
Bank Sta=4993.1,4997.9
XS Rating Curve= 0 ,0
Exp/Cntr=0.3,0.1

Type RM Length L Ch R = 1 ,29024   ,291,291,291
BEGIN DESCRIPTION:
Elm 02 23 29024.17
END DESCRIPTION:
XS GIS Cut Line= 3
      1622914.72      6843396.69        1623212.      6843581.13
      1623576.05      6843843.33
#Sta/Elev= 30
  4649.5 1820.12  4722.4 1819.06    4759 1818.99  4905.5 1814.66  4911.3  1814.8
  4955.8 1813.23  4984.6 1810.35  5003.5 1809.39  5003.8 1808.89  5007.9 1808.89
  5008.3 1809.39  5020.6 1809.85  5035.3 1811.36  5056.2 1810.93  5077.1 1811.22
  5121.2 1810.89  5127.4 1810.41  5150.7 1811.31  5163.3 1812.83  5171.5 1813.12
  5192.4 1812.87  5213.3 1813.55  5242.7 1813.71  5272.2 1814.76  5322.5 1814.42
  5335.8  1815.1  5358.1 1815.31    5379 1816.66  5399.8 1816.24    5448 1816.62
#Mann= 3 ,-1 , 0
  4649.5     .05       0  5003.5     .05       0  5008.3     .05       0
Bank Sta=5003.5,5008.3
XS Rating Curve= 0 ,0
Exp/Cntr=0.3,0.1

Type RM Length L Ch R = 1 ,28733   ,320,320,320
BEGIN DESCRIPTION:
Elm 02 23 28732.64
END DESCRIPTION:
XS GIS Cut Line= 3
      1622699.83      6843650.57      1623053.57       6843815.5
      1623498.43      6843982.59
#Sta/Elev= 30
  4609.2 1816.77    4648 1816.74  4686.3 1815.96  4709.1 1815.96  4737.5 1815.24
  4783.3 1814.94  4806.1 1814.11  4823.5 1814.71  4835.6 1813.77  4851.9 1813.95
  4868.7  1812.7    4926 1811.47  4966.2 1809.25  4971.7 1808.66  5021.9 1808.15
  5022.2 1807.65  5026.3 1807.65  5026.7 1808.15  5043.8 1808.81  5054.5 1808.72
  5118.5 1810.19  5150.6 1811.29  5195.1 1812.05    5220 1813.36  5250.2 1813.31
  5335.6 1814.19  5353.5 1814.88  5390.7 1815.42  5406.9 1816.42  5474.7  1816.6
#Mann= 3 ,-1 , 0
  4609.2     .05       0  5021.9     .03       0  5026.7     .05       0
Bank Sta=5021.9,5026.7
XS Rating Curve= 0 ,0
Exp/Cntr=0.3,0.1

Type RM Length L Ch R = 1 ,28413   ,294,294,294
BEGIN DESCRIPTION:
Elm 02 23 28412.5
END DESCRIPTION:
XS GIS Cut Line= 4
       1622618.5      6843822.42      1622900.65      6844085.03
       1622948.4      6844100.23      1623391.61       6844078.6
#Sta/Elev= 30
  4615.2 1813.97    4666 1812.87  4715.8 1812.66  4765.2 1811.17  4892.7 1809.76
  4913.7 1809.16  4927.9 1808.02    4947 1805.39  4947.3 1804.89  4951.4 1804.89
  4951.8 1805.39  4963.5 1806.52  4970.4 1806.42  4977.7 1809.83  4984.5 1808.09
  4991.9 1810.89  4998.7 1809.48  5015.7 1810.63  5023.9 1810.08  5036.7 1811.22
  5050.8 1810.48  5067.4  1807.9  5077.4  1807.7  5127.5 1809.99  5157.5 1810.28
  5167.5 1811.14  5187.5 1810.99  5437.8 1815.02  5467.9 1816.07  5494.5    1816
#Mann= 3 ,-1 , 0
  4615.2     .05       0    4947     .05       0  4951.8     .05       0
Bank Sta=4947,4951.8
XS Rating Curve= 0 ,0
Exp/Cntr=0.3,0.1

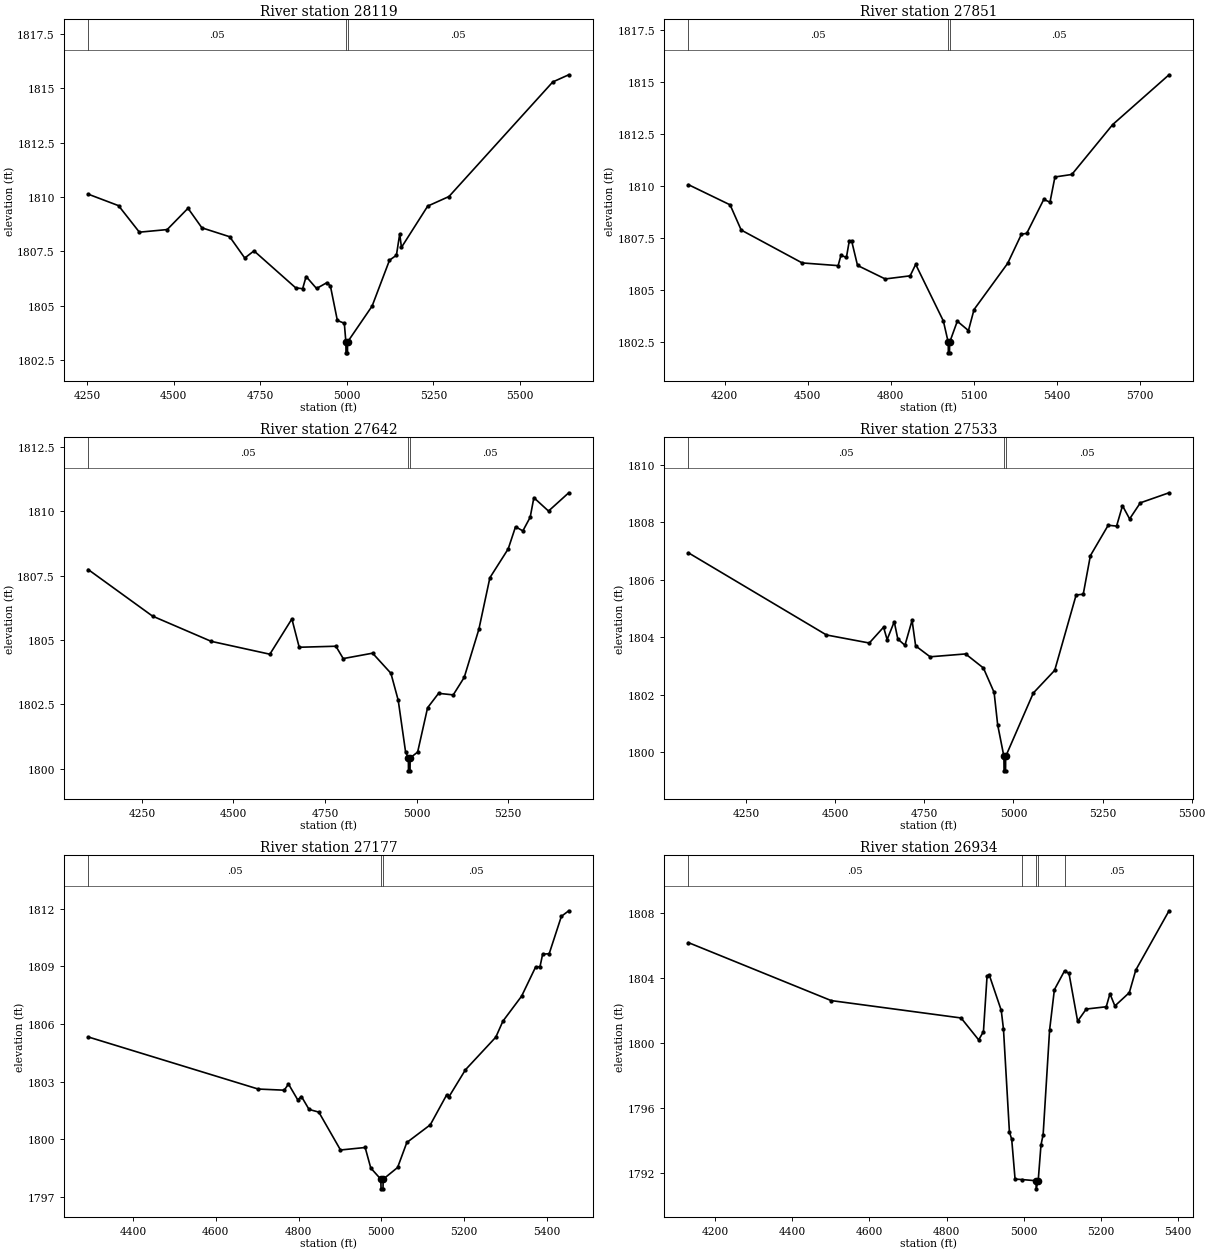
Type RM Length L Ch R = 1 ,28119   ,268,268,268
BEGIN DESCRIPTION:
Elm 02 23 28119.24
END DESCRIPTION:
XS GIS Cut Line= 3
      1622017.45      6844280.35      1622763.93       6844334.6
        1623401.      6844286.93
#Sta/Elev= 30
  4253.3 1810.13  4341.1  1809.6  4401.2 1808.38  4481.5  1808.5  4541.6 1809.48
  4581.7 1808.58  4661.9 1808.17  4705.4 1807.19  4732.1 1807.52  4852.4 1805.82
  4872.5 1805.78  4882.5 1806.34  4912.6 1805.79  4942.7 1806.06  4952.7  1805.9
  4972.7 1804.32  4992.8 1804.19  4997.3 1803.33  4997.7 1802.83  5001.9 1802.83
  5002.2 1803.33    5073 1804.98  5123.2 1807.09  5143.2 1807.32  5152.7  1808.3
  5157.7 1807.68  5233.5 1809.58  5294.9 1810.02  5594.5 1815.29  5640.6 1815.62
#Mann= 3 ,-1 , 0
  4253.3     .05       0  4997.3     .05       0  5002.2     .05       0
Bank Sta=4997.3,5002.2
XS Rating Curve= 0 ,0
Exp/Cntr=0.3,0.1

Type RM Length L Ch R = 1 ,27851   ,209,209,209
BEGIN DESCRIPTION:
Elm 02 23 27851.31
END DESCRIPTION:
XS GIS Cut Line= 3
      1621724.48      6844521.23      1622655.43      6844571.15
      1623454.08      6844466.97
#Sta/Elev= 30
  4068.5 1810.07  4219.2  1809.1  4259.3 1807.89  4479.8 1806.31  4609.8 1806.18
  4619.8 1806.67  4639.8 1806.58  4649.9 1807.35  4658.4 1807.38  4679.9 1806.19
    4780 1805.54  4870.2 1805.69  4890.2 1806.24  4990.3 1803.52    5008 1802.49
  5008.3 1801.99  5012.5 1801.99  5012.9 1802.49  5040.7 1803.51    5081 1803.06
  5101.2 1804.07  5222.8 1806.29  5272.6 1807.69  5291.7 1807.73  5353.3 1809.36
  5375.8 1809.23  5393.7 1810.44  5454.8 1810.56  5602.7 1812.96  5806.2 1815.35
#Mann= 3 ,-1 , 0
  4068.5     .05       0    5008     .05       0  5012.9     .05       0
Bank Sta=5008,5012.9
XS Rating Curve= 0 ,0
Exp/Cntr=0.3,0.1

Type RM Length L Ch R = 1 ,27642   ,109,109,109
BEGIN DESCRIPTION:
Elm 02 23 27642.23
END DESCRIPTION:
XS GIS Cut Line= 3
      1621759.49      6844743.31      1622655.79       6844780.2
      1623070.18      6844773.69
#Sta/Elev= 30
  4103.5 1807.74  4279.2 1805.93  4439.3 1804.95  4599.4 1804.45  4659.5 1805.82
  4679.5 1804.72  4779.6 1804.76  4799.6 1804.28  4879.7 1804.49  4929.7 1803.71
  4949.7 1802.66  4969.7 1800.66  4977.3 1800.42  4977.7 1799.92  4981.9 1799.92
  4982.2 1800.42  5002.7 1800.65  5029.8 1802.37  5059.8 1802.93  5099.8 1802.87
  5129.8 1803.55  5169.8 1805.42  5199.8 1807.42  5249.8 1808.54  5269.8  1809.4
  5289.8 1809.24  5309.8 1809.77  5319.8 1810.53  5359.8 1810.01    5415 1810.72
#Mann= 3 ,-1 , 0
  4103.5     .05       0  4977.3     .03       0  4982.2     .05       0
Bank Sta=4977.3,4982.2
XS Rating Curve= 0 ,0
Exp/Cntr=0.3,0.1

Type RM Length L Ch R = 1 ,27533   ,356,356,356
BEGIN DESCRIPTION:
Elm 02 23 27532.7
END DESCRIPTION:
XS GIS Cut Line= 3
      1621737.87      6844867.01      1622651.45      6844888.71
      1623085.52      6844880.03
#Sta/Elev= 30
  4088.5 1806.94  4475.7 1804.08  4595.8  1803.8  4635.8 1804.35  4645.8 1803.92
  4665.8 1804.54  4675.8 1803.94  4695.8 1803.72  4715.8 1804.59  4725.8  1803.7
  4766.4 1803.32  4865.9 1803.42  4915.9 1802.93  4945.9 1802.08  4955.9 1800.95
  4973.4 1799.85  4973.8 1799.35    4978 1799.35  4978.3 1799.85  5055.9 1802.06
  5115.9 1802.85  5175.9 1805.47  5195.9  1805.5  5215.9 1806.84  5265.9  1807.9
  5289.4 1807.87    5306 1808.58    5326 1808.12    5356 1808.68  5436.5 1809.03
#Mann= 3 ,-1 , 0
  4088.5     .05       0  4973.4     .03       0  4978.3     .05       0
Bank Sta=4973.4,4978.3
XS Rating Curve= 0 ,0
Exp/Cntr=0.3,0.1

Type RM Length L Ch R = 1 ,27177   ,243,243,243
BEGIN DESCRIPTION:
Elm 02 23 27177.35
END DESCRIPTION:
XS GIS Cut Line= 3
      1621822.47       6844984.2      1622501.71       6845194.7
      1622907.55      6845390.02
#Sta/Elev= 30
  4291.5 1805.33  4702.4 1802.62  4765.4 1802.56  4775.7 1802.88    4798 1802.06
  4807.1 1802.23  4825.4 1801.56    4849 1801.42  4901.4 1799.45    4961 1799.58
  4974.6 1798.51  4998.9 1797.93  4999.4 1797.43  5004.1 1797.43  5004.5 1797.93
  5039.4 1798.54  5061.7 1799.84  5118.4 1800.76  5158.1 1802.32  5163.6 1802.22
  5203.3 1803.62  5276.8 1805.32  5293.9 1806.15  5339.1 1807.45  5372.8 1808.96
  5383.6 1808.99  5389.9 1809.63  5405.8 1809.66  5435.2  1811.6    5453 1811.89
#Mann= 3 ,-1 , 0
  4291.5     .05       0  4998.9     .03       0  5004.5     .05       0
Bank Sta=4998.9,5004.5
XS Rating Curve= 0 ,0
Exp/Cntr=0.3,0.1

Type RM Length L Ch R = 1 ,26934   ,390,390,390
BEGIN DESCRIPTION:
Elm 02 23 26933.66
END DESCRIPTION:
XS GIS Cut Line= 4
      1621601.09      6845077.51      1622278.18      6845322.74
      1622404.05      6845400.86      1622740.21      6845570.02
#Sta/Elev= 30
  4131.6  1806.2  4501.4 1802.63  4837.7 1801.56  4883.3 1800.21  4895.6 1800.72
    4905 1804.15  4910.9 1804.19  4941.7 1802.03  4947.5 1800.87  4962.9 1794.54
  4968.8 1794.09  4977.5 1791.64  4996.1 1791.61  5031.7 1791.54  5032.2 1791.04
  5037.4 1791.54  5044.6 1793.74  5050.2 1794.38  5066.9 1800.81  5079.3  1803.3
  5105.6 1804.46  5117.2  1804.3  5139.5 1801.36  5161.8 1802.11  5213.6 1802.25
  5223.2 1803.05    5236  1802.3  5273.4 1803.12  5290.1 1804.51  5376.2 1808.16
#Mann= 5 ,-1 , 0
  4131.6     .05       0  4996.1     .12       0  5031.7     .07       0
  5037.4     .12       0  5105.6     .05       0
Bank Sta=5031.7,5037.4
XS Rating Curve= 0 ,0
Exp/Cntr=0.3,0.1

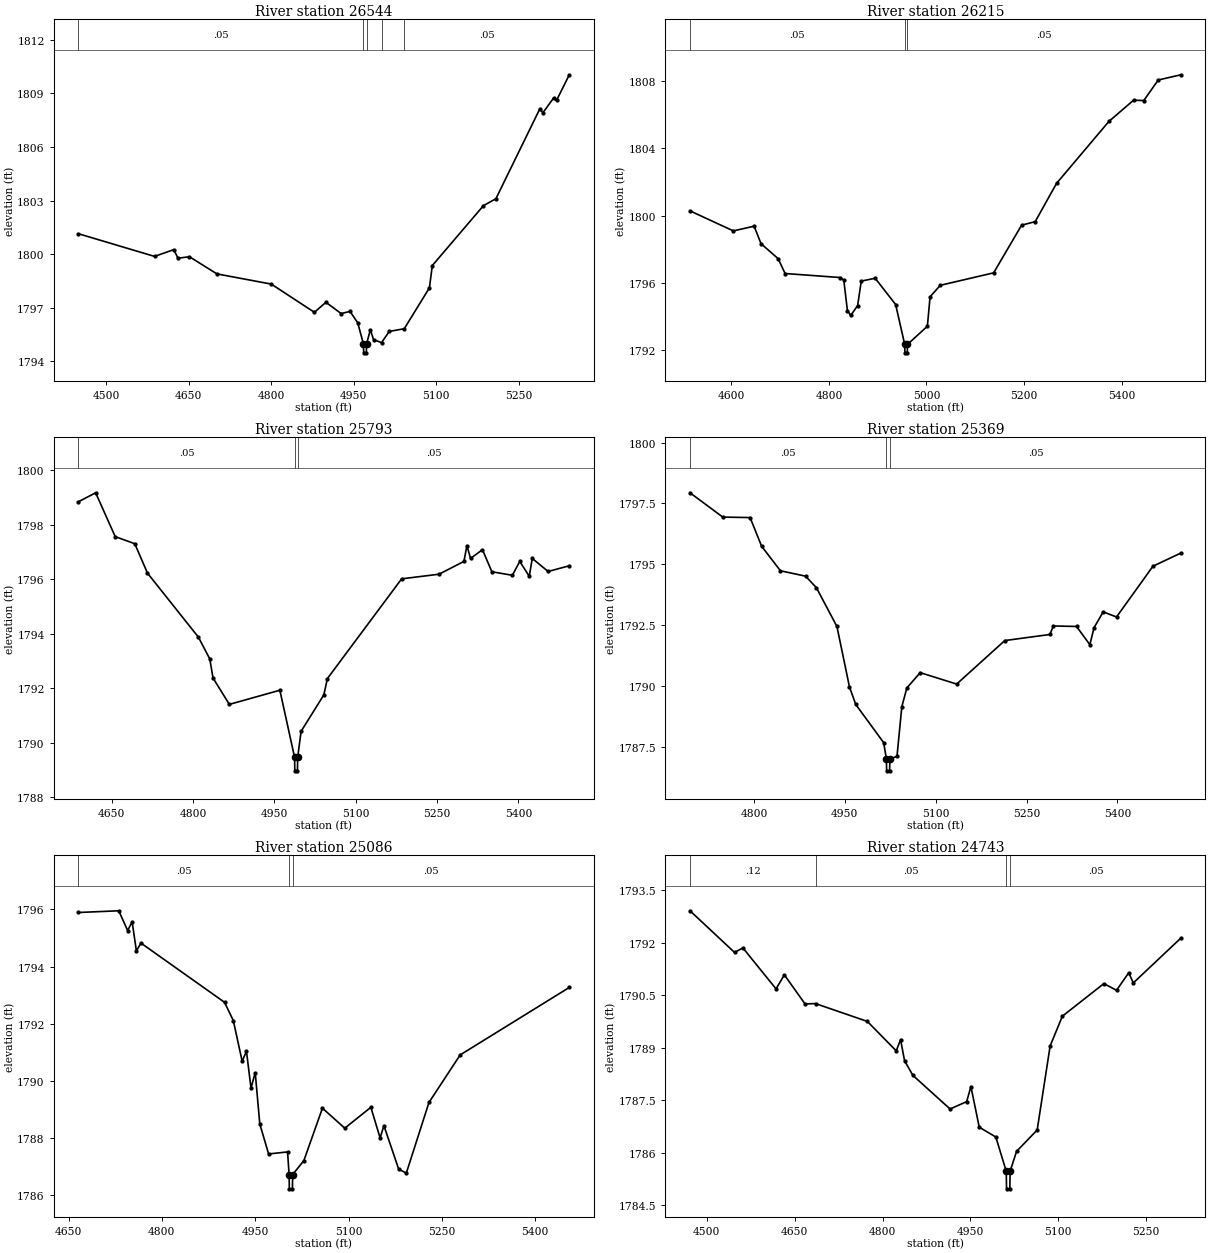
Type RM Length L Ch R = 1 ,26544   ,329,329,329
BEGIN DESCRIPTION:
Elm 02 23 26544.2
END DESCRIPTION:
XS GIS Cut Line= 4
      1621906.24      6845361.38      1622229.14      6845712.93
      1622294.24      6845751.99      1622611.01      6845871.43
#Sta/Elev= 30
  4449.7 1801.14    4588 1799.87  4623.1 1800.25  4630.5 1799.77  4651.5 1799.85
  4701.4 1798.89  4800.1 1798.32  4878.4 1796.74  4899.4  1797.3    4927 1796.67
  4943.2 1796.79  4957.2 1796.15  4967.5 1794.97    4968 1794.47  4972.8 1794.47
  4973.2 1794.97  4980.1 1795.76  4985.9 1795.21  5000.4 1795.04  5014.5 1795.67
  5041.7 1795.82  5087.4 1798.11  5092.7 1799.36  5185.5 1802.71  5208.2  1803.1
  5288.1 1808.14  5293.5 1807.91    5313 1808.74  5318.3  1808.6  5341.5 1810.04
#Mann= 5 ,-1 , 0
  4449.7     .05       0  4967.5     .05       0  4973.2     .05       0
  5000.4     .12       0  5041.7     .05       0
Bank Sta=4967.5,4973.2
XS Rating Curve= 0 ,0
Exp/Cntr=0.3,0.1

Type RM Length L Ch R = 1 ,26215   ,422,422,422
BEGIN DESCRIPTION:
Elm 02 23 26215.43
END DESCRIPTION:
XS GIS Cut Line= 3
      1621661.46      6845595.77      1622023.41      6845921.26
      1622450.24      6846217.96
#Sta/Elev= 30
  4515.1 1800.29    4604  1799.1  4646.6 1799.38  4660.8 1798.34  4695.9 1797.45
  4710.1 1796.57  4823.7 1796.33  4830.5 1796.17  4837.9 1794.37  4844.7 1794.08
  4858.9 1794.67  4866.3 1796.12  4894.8 1796.29  4936.8 1794.73  4955.4 1792.36
  4955.9 1791.86  4960.7 1791.86  4961.1 1792.36  5001.9 1793.44  5007.4 1795.19
  5028.4 1795.87  5137.8 1796.61  5195.1 1799.44    5223 1799.65  5266.7 1801.92
  5374.1  1805.6  5424.7 1806.86  5445.6 1806.84  5475.3 1808.06  5521.7 1808.37
#Mann= 3 ,-1 , 0
  4515.1     .05       0  4955.4     .05       0  4961.1     .05       0
Bank Sta=4955.4,4961.1
XS Rating Curve= 0 ,0
Exp/Cntr=0.3,0.1

Type RM Length L Ch R = 1 ,25793   ,424,424,424
BEGIN DESCRIPTION:
Elm 02 23 25793.44
END DESCRIPTION:
XS GIS Cut Line= 3
      1621475.44      6845841.88      1621703.33       6846184.8
      1621909.24      6846633.47
#Sta/Elev= 30
  4588.6 1798.85  4620.4 1799.18  4656.5 1797.57  4692.6 1797.31    4716 1796.23
  4809.9 1793.88  4830.9 1793.08  4836.9 1792.38    4867 1791.41  4960.2 1791.93
  4987.3 1789.47  4987.8 1788.97  4992.6 1788.97  4993.1 1789.47  4999.3 1790.42
  5041.3 1791.76  5047.9 1792.36  5184.8 1796.02  5253.8 1796.19  5299.7 1796.66
  5305.2 1797.24  5311.9 1796.77  5333.9 1797.09  5351.2 1796.28    5389 1796.15
  5402.7 1796.66  5420.2 1796.11  5425.7 1796.77    5455 1796.29    5494  1796.5
#Mann= 3 ,-1 , 0
  4588.6     .05       0  4987.3     .05       0  4993.1     .05       0
Bank Sta=4987.3,4993.1
XS Rating Curve= 0 ,0
Exp/Cntr=0.3,0.1

Type RM Length L Ch R = 1 ,25369   ,283,283,283
BEGIN DESCRIPTION:
Elm 02 23 25369.1
END DESCRIPTION:
XS GIS Cut Line= 3
      1621215.04      6845943.89      1621295.34      6846241.23
      1621531.07      6846684.56
#Sta/Elev= 30
  4694.5 1797.94  4748.6 1796.94  4793.7 1796.92  4812.7 1795.74  4843.8 1794.73
  4885.2 1794.51    4903 1794.04    4937 1792.44  4957.7 1789.95  4968.1 1789.23
  5014.1 1787.66  5018.6    1787    5019  1786.5  5023.9  1786.5  5024.4    1787
  5036.1 1787.09  5044.1 1789.14  5052.4 1789.91  5074.4 1790.54  5134.6 1790.07
    5214 1791.86  5288.5 1792.11  5294.1 1792.46  5332.4 1792.44  5354.4 1791.69
  5361.3 1792.39  5376.4 1793.04  5398.4 1792.83  5458.6 1794.92  5504.6 1795.46
#Mann= 3 ,-1 , 0
  4694.5     .05       0  5018.6     .05       0  5024.4     .05       0
Bank Sta=5018.6,5024.4
XS Rating Curve= 0 ,0
Exp/Cntr=0.3,0.1

Type RM Length L Ch R = 1 ,25086   ,343,343,343
BEGIN DESCRIPTION:
Elm 02 23 25086.04
END DESCRIPTION:
XS GIS Cut Line= 3
      1620790.45      6846080.66      1621035.65      6846310.67
      1621291.75      6846683.97
#Sta/Elev= 30
  4665.9 1795.89  4730.8 1795.95    4745 1795.26  4752.3 1795.56  4759.1 1794.55
  4766.5 1794.82  4900.8 1792.75  4914.9 1792.11  4929.1 1790.69    4936 1791.04
  4943.3 1789.75  4950.1 1790.29  4957.4  1788.5  4971.6 1787.45  5002.1 1787.52
  5004.5 1786.73  5004.9 1786.23  5009.8 1786.23  5010.3 1786.73  5028.3 1787.22
  5058.1 1789.05    5094 1788.35  5135.9 1789.08  5150.8 1788.01  5156.9 1788.44
  5180.6 1786.92  5192.9 1786.78  5229.3 1789.25  5279.4 1790.91  5454.8 1793.27
#Mann= 3 ,-1 , 0
  4665.9     .05       0  5004.5     .05       0  5010.3     .05       0
Bank Sta=5004.5,5010.3
XS Rating Curve= 0 ,0
Exp/Cntr=0.3,0.1

Type RM Length L Ch R = 1 ,24743   ,594,594,594
BEGIN DESCRIPTION:
Elm 02 23 24742.76
END DESCRIPTION:
XS GIS Cut Line= 3
      1620521.35      6846223.89      1620907.61      6846584.11
      1621146.34       6846781.6
#Sta/Elev= 30
  4471.2 1792.91  4547.3 1791.72  4561.5 1791.85  4618.1 1790.68  4632.3 1791.08
  4667.6 1790.25  4685.5 1790.26    4774 1789.75  4823.3 1788.91  4830.7 1789.23
  4837.5 1788.63  4851.7 1788.21  4915.2 1787.25  4943.5 1787.46  4950.8 1787.89
    4965 1786.73  4993.3 1786.45  5011.1 1785.47  5011.6 1784.97  5017.2 1784.97
  5017.7 1785.47  5028.7 1786.04  5063.9 1786.65    5086 1789.05  5106.9  1789.9
  5177.7 1790.83  5199.4 1790.64  5220.2 1791.14    5228 1790.85  5309.2 1792.13
#Mann= 4 ,-1 , 0
  4471.2     .12       0  4685.5     .05       0  5011.1     .05       0
  5017.7     .05       0
Bank Sta=5011.1,5017.7
XS Rating Curve= 0 ,0
Exp/Cntr=0.3,0.1

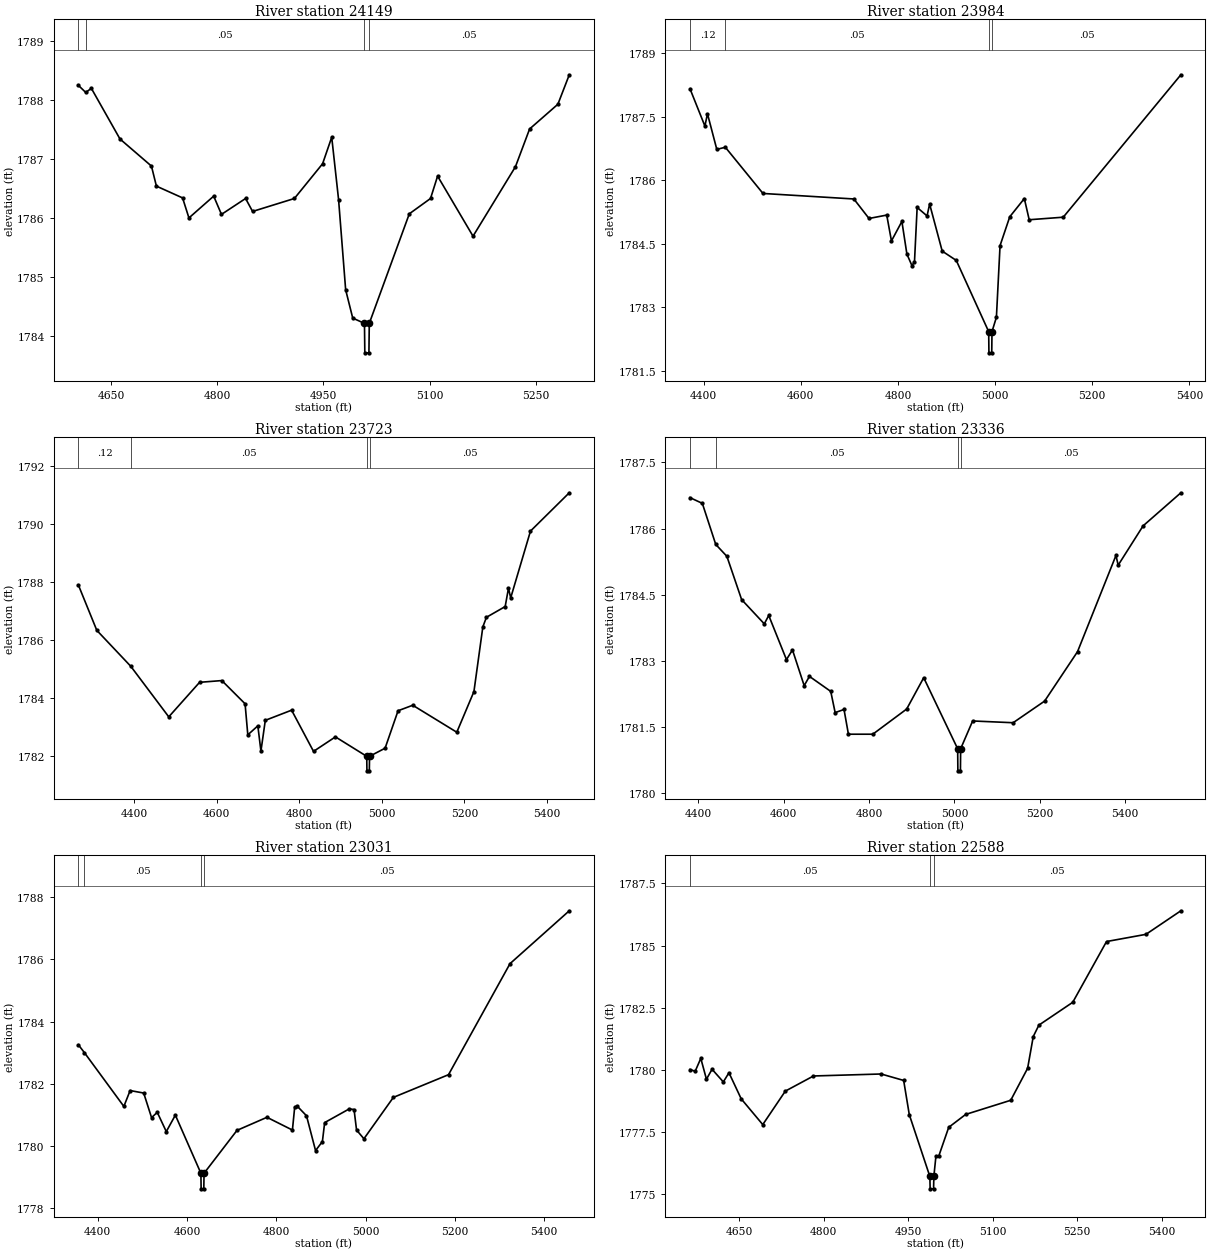
Type RM Length L Ch R = 1 ,24149   ,165,165,165
BEGIN DESCRIPTION:
Elm 02 23 24148.68
END DESCRIPTION:
XS GIS Cut Line= 4
      1620263.43      6846434.08      1620410.65      6846755.54
      1620455.01      6846756.79      1620751.13      6846761.12
#Sta/Elev= 30
  4603.5 1788.25  4613.9 1788.13  4621.8  1788.2  4662.3 1787.34  4706.8 1786.88
  4713.8 1786.54  4750.8 1786.34  4759.8    1786  4794.8 1786.37  4805.8 1786.06
  4839.9 1786.33  4849.8 1786.11  4908.9 1786.33  4948.8 1786.92  4961.7 1787.37
  4971.4 1786.31  4981.4 1784.78  4991.4  1784.3    5008 1784.21  5008.5 1783.71
  5014.3 1783.71  5014.8 1784.21  5071.4 1786.07  5101.4 1786.33  5111.4 1786.71
  5161.5 1785.69  5221.5 1786.87  5241.5 1787.51  5281.5 1787.93  5297.6 1788.43
#Mann= 4 ,-1 , 0
  4603.5     .12       0  4613.9     .05       0    5008     .05       0
  5014.8     .05       0
Bank Sta=5008,5014.8
XS Rating Curve= 0 ,0
Exp/Cntr=0.3,0.1

Type RM Length L Ch R = 1 ,23984   ,261,261,261
BEGIN DESCRIPTION:
Elm 02 23 23983.52
END DESCRIPTION:
XS GIS Cut Line= 4
      1620129.32      6846415.84      1620299.99      6846910.53
      1620405.09      6846906.53      1620787.08      6846919.56
#Sta/Elev= 30
  4371.9 1788.16  4402.6 1787.28  4407.9 1787.57  4427.1 1786.73  4444.7 1786.78
  4522.2 1785.69  4709.3 1785.56  4740.5  1785.1    4777 1785.18  4786.7 1784.57
  4808.2 1785.03  4818.5 1784.26  4828.8 1783.99  4834.1 1784.07  4839.6 1785.36
    4860 1785.16  4865.3 1785.44  4891.2 1784.33  4920.2 1784.11  4986.9 1782.43
  4987.4 1781.93  4993.2 1781.93  4993.7 1782.43  5002.8 1782.77  5010.3 1784.46
  5030.3 1785.14  5060.3 1785.57  5070.3 1785.07  5140.4 1785.13  5382.6 1788.49
#Mann= 4 ,-1 , 0
  4371.9     .12       0  4444.7     .05       0  4986.9     .03       0
  4993.7     .05       0
Bank Sta=4986.9,4993.7
XS Rating Curve= 0 ,0
Exp/Cntr=0.3,0.1

Type RM Length L Ch R = 1 ,23723   ,387,387,387
BEGIN DESCRIPTION:
Elm 02 23 23723.1
END DESCRIPTION:
XS GIS Cut Line= 4
      1619924.88      6846431.44      1620139.49       6847033.8
      1620233.65      6847064.95       1620405.1      6847481.62
#Sta/Elev= 30
  4264.7  1787.9  4309.3 1786.34  4391.7  1785.1  4483.6 1783.36  4558.3 1784.55
  4612.2 1784.61  4668.5 1783.81  4675.1 1782.74  4699.4 1783.05  4706.9 1782.18
  4717.5 1783.24  4781.2 1783.59  4834.3 1782.17  4887.4 1782.67  4963.2    1782
  4963.7  1781.5  4969.5  1781.5    4970    1782  5007.7 1782.28  5039.1 1783.57
  5074.7 1783.76  5181.4 1782.83  5222.9 1784.23  5244.5 1786.46  5253.2 1786.79
  5298.6 1787.16  5306.6 1787.79    5312 1787.46  5359.9 1789.76  5453.9 1791.08
#Mann= 4 ,-1 , 0
  4264.7     .12       0  4391.7     .05       0  4963.2     .05       0
    4970     .05       0
Bank Sta=4963.2,4970
XS Rating Curve= 0 ,0
Exp/Cntr=0.3,0.1

Type RM Length L Ch R = 1 ,23336   ,305,305,305
BEGIN DESCRIPTION:
Elm 02 23 23335.87
END DESCRIPTION:
XS GIS Cut Line= 3
      1619687.06      6846490.12      1619851.06      6847089.69
      1620016.43      6847591.03
#Sta/Elev= 30
  4380.8  1786.7  4409.7 1786.57  4441.1 1785.64  4467.2 1785.37  4501.7 1784.39
  4554.8 1783.84  4565.2 1784.03  4606.7 1783.03  4620.8 1783.25  4648.2 1782.44
  4660.5 1782.65  4710.4 1782.31  4720.7 1781.83  4741.5  1781.9  4751.8 1781.34
  4808.9 1781.34  4888.2 1781.91  4928.1 1782.62  5007.6 1781.01  5008.1 1780.51
  5014.1 1780.51  5014.6 1781.01  5042.7 1781.64  5137.5  1781.6  5211.2 1782.09
  5288.3 1783.21  5378.3 1785.39  5383.5 1785.17  5441.8 1786.06  5530.3 1786.81
#Mann= 4 ,-1 , 0
  4380.8     .12       0  4441.1     .05       0  5007.6    .035       0
  5014.6     .05       0
Bank Sta=5007.6,5014.6
XS Rating Curve= 0 ,0
Exp/Cntr=0.3,0.1

Type RM Length L Ch R = 1 ,23031   ,443,443,443
BEGIN DESCRIPTION:
Elm 02 23 23031.27
END DESCRIPTION:
XS GIS Cut Line= 5
      1619573.76      6846663.65      1619662.66      6847219.89
      1619700.41       6847292.3      1619743.23      6847406.02
      1619770.82       6847737.5
#Sta/Elev= 30
  4357.1 1783.25  4370.5    1783  4458.9 1781.27  4472.9 1781.78  4503.3  1781.7
  4520.9 1780.91  4533.7 1781.08  4553.9 1780.46  4574.2 1780.99  4631.4 1779.12
  4631.9 1778.62  4637.9 1778.62  4638.4 1779.12  4712.2  1780.5  4779.3 1780.92
  4836.3 1780.51  4841.4 1781.25  4847.6 1781.27  4867.8 1780.97  4888.1 1779.85
  4903.4 1780.14  4908.5 1780.75  4963.5 1781.19  4974.3 1781.17  4979.9 1780.51
  4996.4 1780.23  5062.3 1781.56  5185.8 1782.29  5323.5 1785.86  5456.2 1787.56
#Mann= 4 ,-1 , 0
  4357.1     .12       0  4370.5     .05       0  4631.4     .05       0
  4638.4     .05       0
Bank Sta=4631.4,4638.4
XS Rating Curve= 0 ,0
Exp/Cntr=0.3,0.1

Type RM Length L Ch R = 1 ,22588   ,360,360,360
BEGIN DESCRIPTION:
Elm 02 23 22587.81
END DESCRIPTION:
XS GIS Cut Line= 3
      1619393.11      6846798.85      1619377.49      6847237.61
      1619391.81      6847669.93
#Sta/Elev= 30
  4562.5    1780  4571.7 1779.93  4581.7 1780.45  4591.7 1779.61  4601.7 1780.01
  4621.7  1779.5  4631.7 1779.87  4653.4 1778.82  4691.7 1777.78  4731.8 1779.13
  4781.8 1779.74  4901.9 1779.82  4941.9 1779.56  4951.9 1778.18  4988.4 1775.69
  4988.9 1775.19    4995 1775.19  4995.5 1775.69  4999.2 1776.51  5004.2 1776.51
  5021.9 1777.67    5052 1778.19    5132 1778.76    5162 1780.05    5172 1781.33
    5182 1781.79  5242.1 1782.71  5302.1 1785.16  5372.1 1785.45  5434.1  1786.4
#Mann= 3 ,-1 , 0
  4562.5     .05       0  4988.4     .05       0  4995.5     .05       0
Bank Sta=4988.4,4995.5
XS Rating Curve= 0 ,0
Exp/Cntr=0.3,0.1