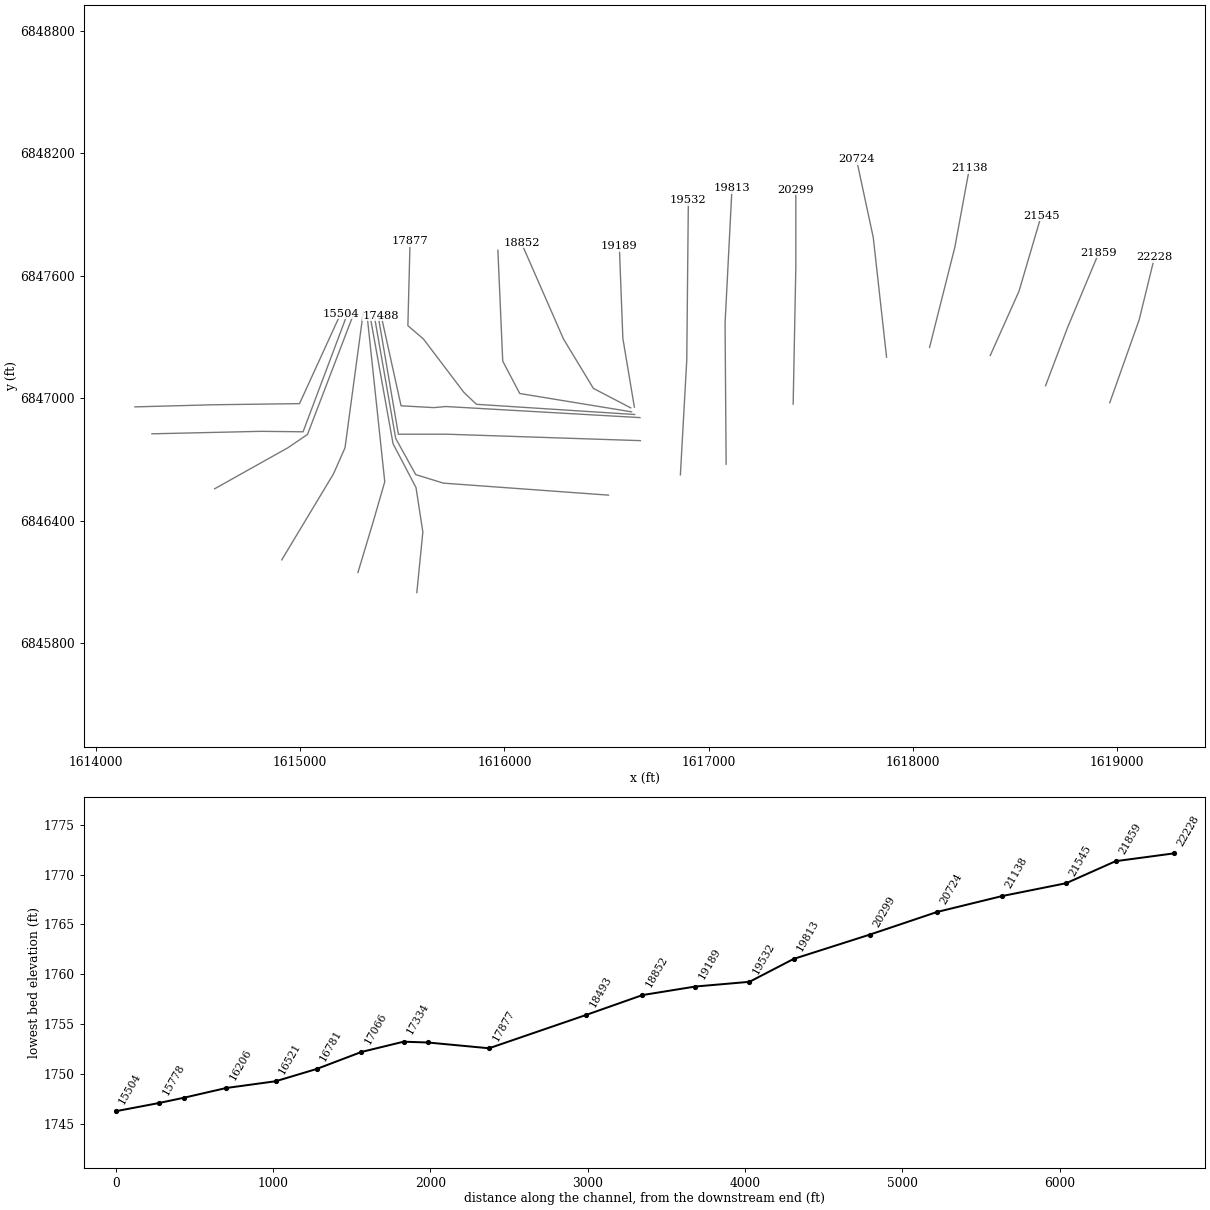
HEC-RAS study Elm 02 23.prj: Elm 02 23 Base Level Engineering

--- Elm 02 23.g01 (geometry) --- (continued)

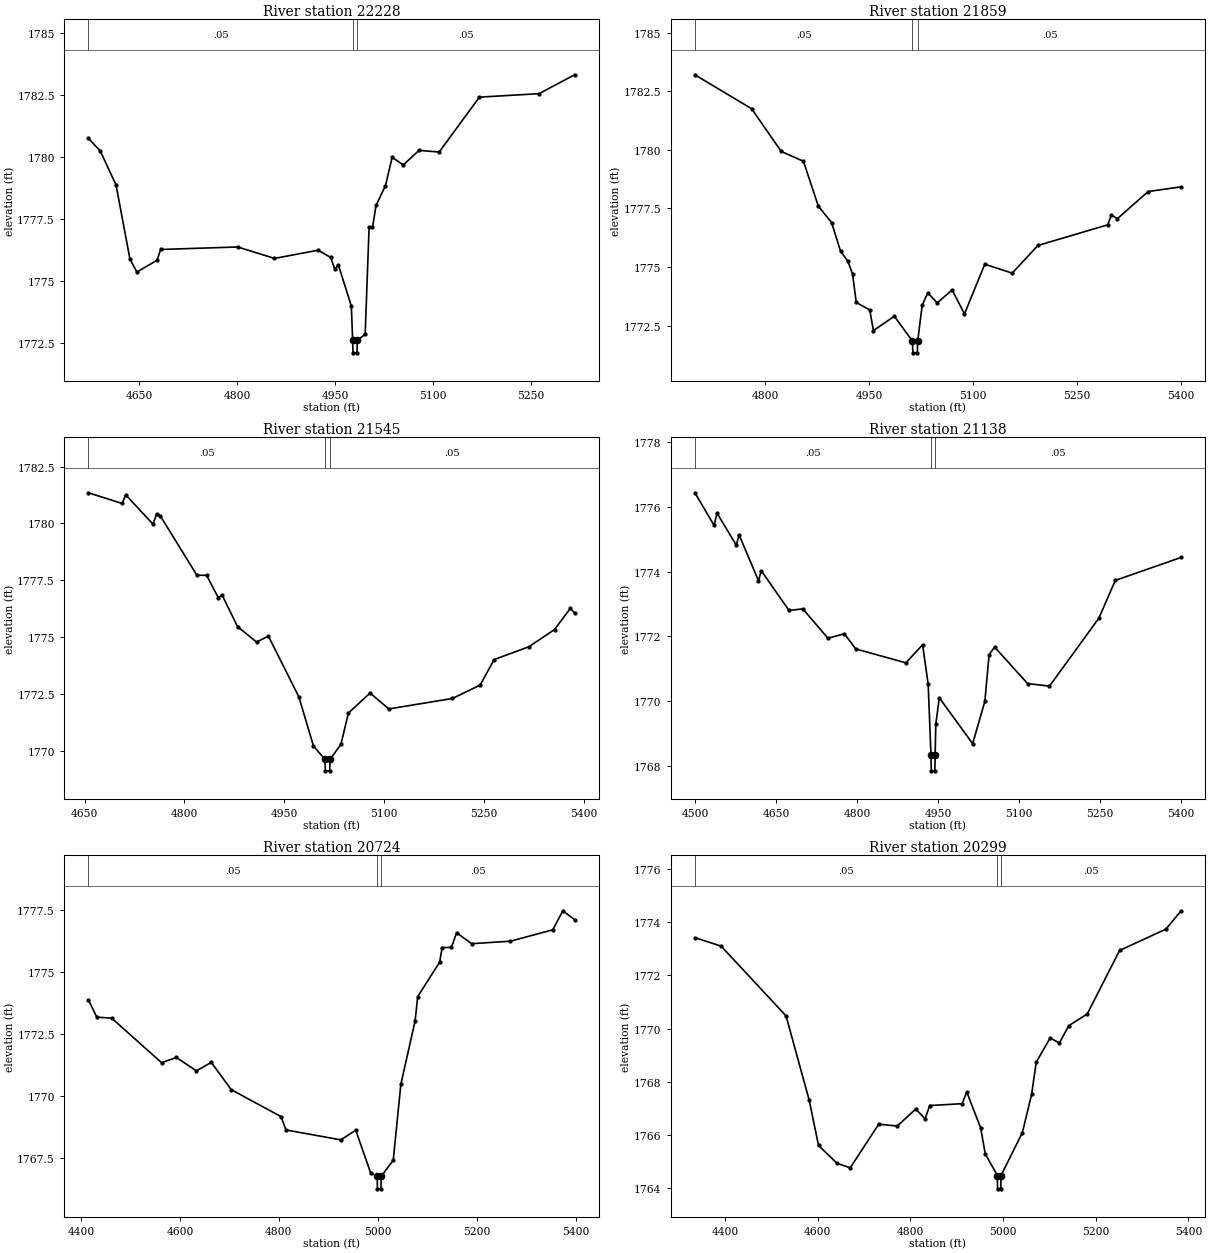
Type RM Length L Ch R = 1 ,22228   ,369,369,369
BEGIN DESCRIPTION:
Elm 02 23 22228.18
END DESCRIPTION:
XS GIS Cut Line= 3
      1618963.25        6846978.      1619107.35      6847384.27
        1619182.      6847689.82
#Sta/Elev= 30
    4572 1780.75  4590.1 1780.25  4614.4 1778.87  4635.7 1775.89  4646.3 1775.37
  4677.4 1775.85  4682.7 1776.28  4800.9 1776.38  4857.3 1775.92  4924.3 1776.25
  4943.4 1775.96  4949.9 1775.48  4955.2 1775.67  4975.2    1774  4977.2 1772.62
  4977.7 1772.12  4983.8 1772.12  4984.3 1772.62  4996.4 1772.87  5002.4 1777.17
  5007.6 1777.17  5013.1 1778.05  5027.5 1778.85  5037.8 1779.99  5054.8 1779.68
    5079 1780.27  5109.8  1780.2  5171.6 1782.41  5263.1 1782.55  5317.6 1783.31
#Mann= 3 ,-1 , 0
    4572     .05       0  4977.2     .05       0  4984.3     .05       0
Bank Sta=4977.2,4984.3
XS Rating Curve= 0 ,0
Exp/Cntr=0.3,0.1

Type RM Length L Ch R = 1 ,21859   ,314,314,314
BEGIN DESCRIPTION:
Elm 02 23 21859.1
END DESCRIPTION:
XS GIS Cut Line= 3
      1618649.01      6847061.32      1618756.66      6847346.07
      1618909.98      6847713.01
#Sta/Elev= 30
  4698.7  1783.2  4780.7 1781.75  4823.4 1779.93  4855.5 1779.51  4876.9  1777.6
  4896.2 1776.89    4909 1775.68  4919.7 1775.24  4926.4  1774.7  4931.7 1773.49
  4951.2 1773.17  4956.5 1772.29  4986.7  1772.9  5012.9 1771.84  5013.4 1771.34
  5019.9 1771.34  5020.4 1771.84  5026.9 1773.36    5035  1773.9  5048.6 1773.47
  5070.2 1774.02    5088    1773  5117.3 1775.12  5156.9 1774.74  5194.1 1775.92
  5294.8  1776.8  5300.2 1777.22  5308.7 1777.06  5353.2 1778.22  5400.8 1778.42
#Mann= 3 ,-1 , 0
  4698.7     .05       0  5012.9     .05       0  5020.4     .05       0
Bank Sta=5012.9,5020.4
XS Rating Curve= 0 ,0
Exp/Cntr=0.3,0.1

Type RM Length L Ch R = 1 ,21545   ,407,407,407
BEGIN DESCRIPTION:
Elm 02 23 21544.83
END DESCRIPTION:
XS GIS Cut Line= 3
      1618378.17      6847209.35      1618518.81      6847523.62
      1618627.88       6847894.1
#Sta/Elev= 30
  4655.7 1781.35  4706.3 1780.88  4711.8 1781.26  4752.7 1779.97  4758.2 1780.43
  4763.8 1780.33  4818.6 1777.73  4833.3 1777.72    4851 1776.73  4856.5 1776.86
  4879.7 1775.47  4908.3 1774.79  4926.1 1775.05  4971.9 1772.38  4993.8 1770.22
  5011.2 1769.63  5011.7 1769.13  5018.2 1769.13  5018.7 1769.63  5035.1  1770.3
  5046.3 1771.67  5078.9 1772.55    5107 1771.85  5202.6 1772.31  5244.3  1772.9
  5265.2 1774.02  5317.3 1774.58    5356 1775.34  5379.8 1776.27  5386.2 1776.07
#Mann= 3 ,-1 , 0
  4655.7     .05       0  5011.2     .05       0  5018.7     .05       0
Bank Sta=5011.2,5018.7
XS Rating Curve= 0 ,0
Exp/Cntr=0.3,0.1

Type RM Length L Ch R = 1 ,21138   ,414,414,414
BEGIN DESCRIPTION:
Elm 02 23 21138.44
END DESCRIPTION:
XS GIS Cut Line= 3
      1618081.13      6847248.94      1618204.83      6847739.42
      1618276.44      6848127.83
#Sta/Elev= 30
  4499.4 1776.44  4535.1 1775.43  4540.3 1775.81  4576.2 1774.82  4581.3 1775.14
  4617.2 1773.72  4622.4 1774.03  4673.8  1772.8  4699.4 1772.85  4745.9 1771.94
  4776.4 1772.08  4797.5 1771.61  4890.3 1771.18  4921.3 1771.74  4931.6 1770.52
  4936.8 1768.34  4937.3 1767.84    4944 1767.84  4944.5 1768.34  4945.8 1769.29
  4952.2  1770.1    5014 1768.68  5036.6 1769.99  5044.5 1771.43  5054.6 1771.67
  5115.7 1770.54  5156.3 1770.46  5247.8 1772.56  5278.3 1773.73  5400.2 1774.44
#Mann= 3 ,-1 , 0
  4499.4     .05       0  4936.8     .05       0  4944.5     .05       0
Bank Sta=4936.8,4944.5
XS Rating Curve= 0 ,0
Exp/Cntr=0.3,0.1

Type RM Length L Ch R = 1 ,20724   ,425,425,425
BEGIN DESCRIPTION:
Elm 02 23 20724.27
END DESCRIPTION:
XS GIS Cut Line= 3
      1617870.63      6847201.22      1617805.53      6847787.16
      1617723.07      6848171.26
#Sta/Elev= 30
  4415.2 1773.88  4432.1 1773.18  4462.3 1773.14  4562.9 1771.34  4593.1 1771.55
  4633.3 1771.01  4663.5 1771.35  4703.7 1770.25  4804.4 1769.16  4814.4 1768.62
  4925.1 1768.22  4955.3 1768.61  4985.5 1766.88  4998.7 1766.74  4999.2 1766.24
  5006.2 1766.24  5006.7 1766.74  5031.1  1767.4  5046.5 1770.47  5075.4 1773.04
  5080.5 1774.01  5124.8  1775.4  5129.9 1775.99  5148.8    1776    5159 1776.59
  5189.7 1776.15  5267.8 1776.25  5353.3 1776.71  5373.8 1777.48  5397.6 1777.12
#Mann= 3 ,-1 , 0
  4415.2     .05       0  4998.7     .05       0  5006.7     .05       0
Bank Sta=4998.7,5006.7
XS Rating Curve= 0 ,0
Exp/Cntr=0.3,0.1

Type RM Length L Ch R = 1 ,20299   ,486,486,486
BEGIN DESCRIPTION:
Elm 02 23 20299.46
END DESCRIPTION:
XS GIS Cut Line= 3
      1617413.38       6846971.2       1617426.4      6847637.86
       1617426.4      6848020.67
#Sta/Elev= 30
  4334.6 1773.42  4391.4  1773.1  4531.4 1770.48  4581.4 1767.31  4601.5 1765.61
  4641.5 1764.94  4669.9 1764.77  4731.5 1766.41  4771.5 1766.34  4811.5 1766.98
  4831.5 1766.61  4841.5 1767.11  4911.5 1767.18  4921.5 1767.62  4951.5 1766.27
  4961.5 1765.29  4987.5 1764.48    4988 1763.98    4995 1763.98  4995.5 1764.48
  5041.5 1766.09  5061.5 1767.53  5071.5 1768.74  5101.5 1769.65  5121.5 1769.46
  5141.5 1770.11  5181.5 1770.55  5251.5 1772.94  5351.5 1773.74  5384.2 1774.43
#Mann= 3 ,-1 , 0
  4334.6     .05       0  4987.5     .05       0  4995.5     .05       0
Bank Sta=4987.5,4995.5
XS Rating Curve= 0 ,0
Exp/Cntr=0.3,0.1

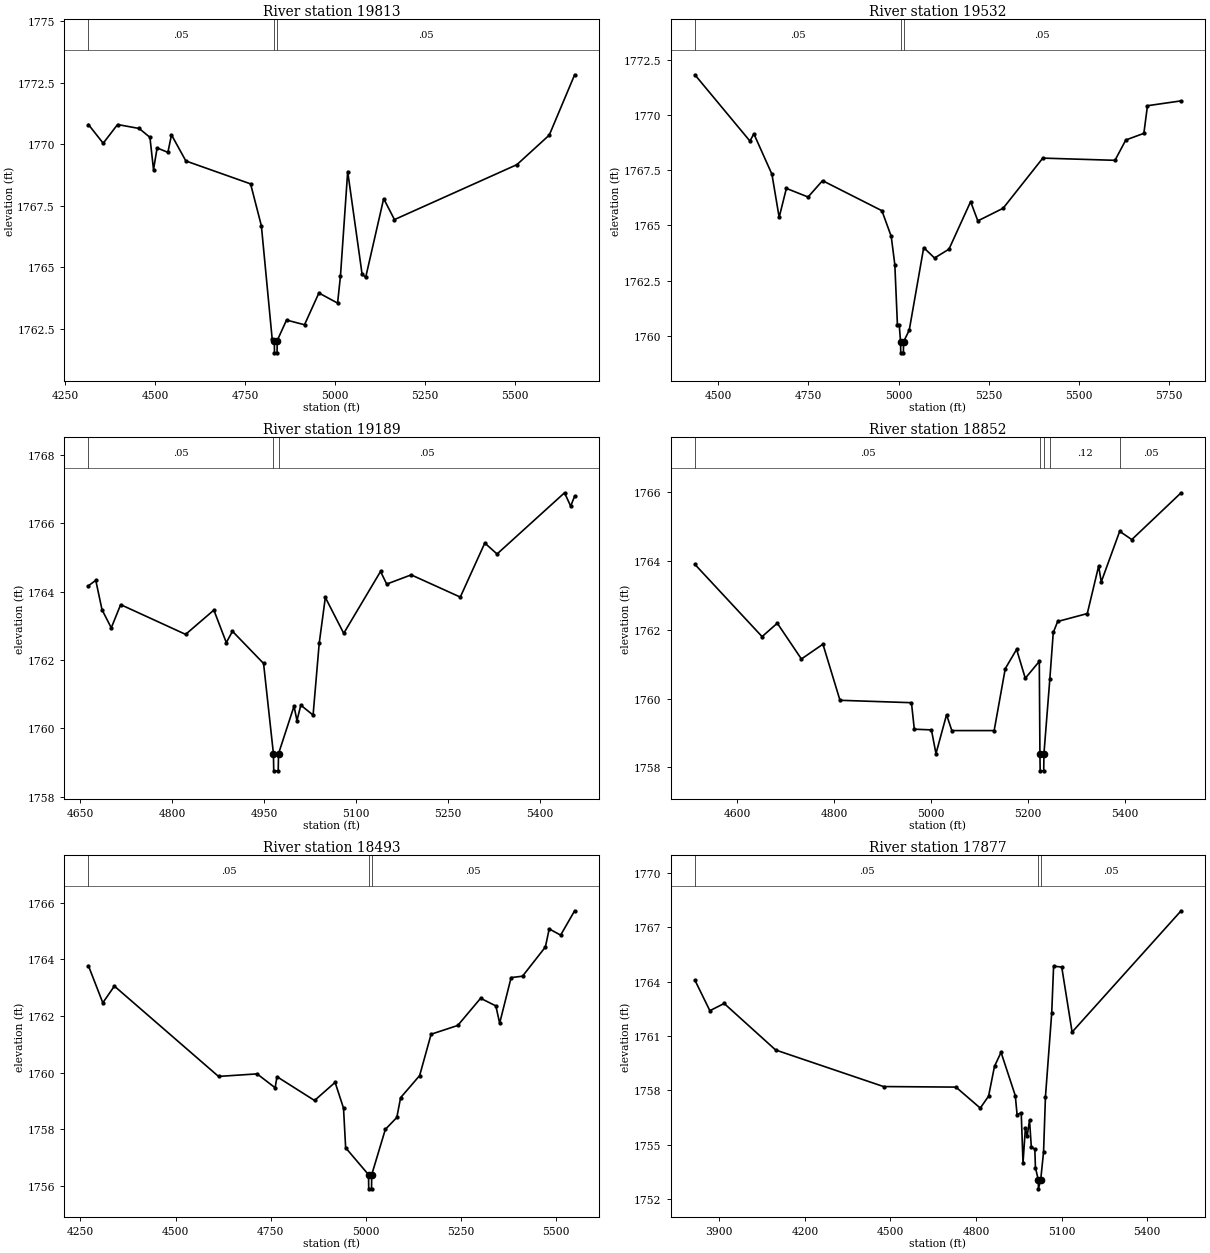
Type RM Length L Ch R = 1 ,19813   ,281,281,281
BEGIN DESCRIPTION:
Elm 02 23 19813.34
END DESCRIPTION:
XS GIS Cut Line= 3
      1617085.26      6846676.89      1617080.05      6847367.02
      1617113.91       6848028.5
#Sta/Elev= 30
  4314.3  1770.8  4355.4 1770.04  4395.4  1770.8  4455.4 1770.64  4485.4 1770.28
  4495.4 1768.97  4505.4 1769.85  4535.4 1769.67  4545.4 1770.38  4585.4 1769.32
  4765.4 1768.39  4795.4 1766.69  4825.4  1762.1  4831.4 1762.03  4831.9 1761.53
    4839 1761.53  4839.5 1762.03  4865.4 1762.86  4915.4 1762.67  4955.4 1763.96
  5007.4 1763.55  5015.4 1764.65  5035.5 1768.89  5075.5 1764.73  5085.5 1764.59
  5135.6 1767.79  5165.6 1766.94  5506.1 1769.17  5596.2 1770.37  5666.8 1772.82
#Mann= 3 ,-1 , 0
  4314.3     .05       0  4831.4     .03       0  4839.5     .05       0
Bank Sta=4831.4,4839.5
XS Rating Curve= 0 ,0
Exp/Cntr=0.3,0.1

Type RM Length L Ch R = 1 ,19532   ,343,343,343
BEGIN DESCRIPTION:
Elm 02 23 19532.04
END DESCRIPTION:
XS GIS Cut Line= 3
       1616861.3      6846624.85      1616892.55      6847187.33
      1616900.36      6847971.15
#Sta/Elev= 30
  4435.7 1771.81  4588.3 1768.81  4599.1 1769.14  4649.2 1767.31  4669.2 1765.36
  4689.2 1766.67  4749.3 1766.28  4789.4 1767.02  4953.9 1765.66  4979.7  1764.5
  4989.7 1763.22  4996.9  1760.5  5001.9  1760.5  5005.6 1759.73  5006.1 1759.23
  5013.4 1759.23  5013.9 1759.73  5029.7 1760.26  5069.7 1763.99  5099.7 1763.52
  5139.7 1763.92  5199.7 1766.07  5219.7  1765.2  5289.7 1765.77  5399.7 1768.04
  5599.7 1767.94  5629.7 1768.86  5679.7 1769.16  5689.7 1770.41  5782.9 1770.63
#Mann= 3 ,-1 , 0
  4435.7     .05       0  5005.6     .05       0  5013.9     .05       0
Bank Sta=5005.6,5013.9
XS Rating Curve= 0 ,0
Exp/Cntr=0.3,0.1

Type RM Length L Ch R = 1 ,19189   ,337,337,337
BEGIN DESCRIPTION:
Elm 02 23 19189.14
END DESCRIPTION:
XS GIS Cut Line= 3
      1616636.17      6846956.12      1616579.74       6847292.5
      1616562.44      6847744.49
#Sta/Elev= 30
  4663.6 1764.17  4675.6 1764.33  4685.8 1763.47  4700.9 1762.94  4716.2 1763.62
  4822.2 1762.75  4868.3 1763.46  4888.6 1762.51  4898.7 1762.84  4949.4  1761.9
  4965.5 1759.26    4966 1758.76  4973.3 1758.76  4973.8 1759.26  4999.1 1760.65
  5003.9 1760.23  5010.2 1760.68  5030.2 1760.39  5040.2 1762.49  5050.2 1763.83
  5080.2 1762.78  5140.3 1764.59  5150.3 1764.22  5190.3 1764.49  5270.4 1763.84
  5310.4 1765.42  5330.4  1765.1  5440.5 1766.89  5450.5  1766.5    5457 1766.79
#Mann= 3 ,-1 , 0
  4663.6     .05       0  4965.5     .03       0  4973.8     .05       0
Bank Sta=4965.5,4973.8
XS Rating Curve= 0 ,0
Exp/Cntr=0.3,0.1

Type RM Length L Ch R = 1 ,18852   ,359,359,359
BEGIN DESCRIPTION:
Elm 02 23 18852.21
END DESCRIPTION:
XS GIS Cut Line= 4
       1616617.9      6846952.89      1616435.34      6847048.22
      1616288.94      6847290.33       1616082.8      6847761.21
#Sta/Elev= 30
  4512.8  1763.9  4651.4  1761.8  4682.8 1762.19  4732.5 1761.15  4776.9 1761.58
  4812.1 1759.95  4959.5 1759.88  4965.4 1759.11  5000.7 1759.09  5010.1  1758.4
  5031.9 1759.53  5042.8 1759.07  5130.1 1759.07    5153 1760.87  5176.4 1761.43
  5194.3 1760.59  5223.2 1761.08  5224.5  1758.4    5225  1757.9  5232.3  1757.9
  5232.8  1758.4    5245 1760.58    5252 1761.92  5261.1 1762.24  5322.2 1762.47
  5345.6 1763.85    5351 1763.39    5389 1764.86    5414 1764.62  5515.7 1765.98
#Mann= 5 ,-1 , 0
  4512.8     .05       0  5224.5     .05       0  5232.8     .05       0
    5245     .12       0    5389     .05       0
Bank Sta=5224.5,5232.8
XS Rating Curve= 0 ,0
Exp/Cntr=0.3,0.1

Type RM Length L Ch R = 1 ,18493   ,616,616,616
BEGIN DESCRIPTION:
Elm 02 23 18493.11
END DESCRIPTION:
XS GIS Cut Line= 4
      1616622.26      6846933.36      1616074.86      6847023.11
      1615991.64      6847181.82      1615967.84      6847724.78
#Sta/Elev= 30
  4270.9 1763.78  4308.7 1762.47  4339.1 1763.06  4612.7 1759.87    4714 1759.96
  4761.4 1759.47  4766.4 1759.86    4865 1759.02    4919 1759.66  4941.1 1758.75
  4946.7 1757.35  5006.8  1756.4  5007.3  1755.9  5014.7  1755.9  5015.2  1756.4
    5051    1758  5081.1 1758.42  5091.1 1759.12  5141.1  1759.9  5171.2 1761.36
  5241.2 1761.67  5301.3 1762.63  5341.3 1762.36  5351.3 1761.75  5381.4 1763.36
  5411.4 1763.41  5471.4 1764.44  5481.5 1765.08  5511.5 1764.86  5548.3 1765.72
#Mann= 3 ,-1 , 0
  4270.9     .05       0  5006.8     .05       0  5015.2     .05       0
Bank Sta=5006.8,5015.2
XS Rating Curve= 0 ,0
Exp/Cntr=0.3,0.1

Type RM Length L Ch R = 1 ,17877   ,389,389,389
BEGIN DESCRIPTION:
Elm 02 23 17877.4
END DESCRIPTION:
XS GIS Cut Line= 6
      1616637.42      6846920.34      1615862.68      6846970.25
      1615800.72      6847029.58      1615603.18      6847290.33
      1615527.23      6847355.43      1615538.08       6847769.9
#Sta/Elev= 30
  3814.7 1764.09  3867.2  1762.4  3917.3  1762.8  4097.7 1760.23  4475.8 1758.21
  4729.5 1758.18  4814.8 1757.02  4843.9 1757.68  4864.7 1759.33  4887.6  1760.1
  4937.5 1757.71  4943.8 1756.66  4958.3 1756.76  4964.6 1753.99  4972.9  1755.9
  4979.2 1755.48  4987.4 1756.35  4993.7 1754.87    5006 1754.75  5008.1 1753.73
  5018.1 1753.06  5018.6 1752.56  5026.6 1753.06  5036.6  1754.6  5043.2 1757.64
  5065.2 1762.28  5071.8 1764.86  5100.3 1764.81  5136.6 1761.22  5518.6 1767.92
#Mann= 3 ,-1 , 0
  3814.7     .05       0  5018.1     .05       0  5026.6     .05       0
Bank Sta=5018.1,5026.6
XS Rating Curve= 0 ,0
Exp/Cntr=0.3,0.1

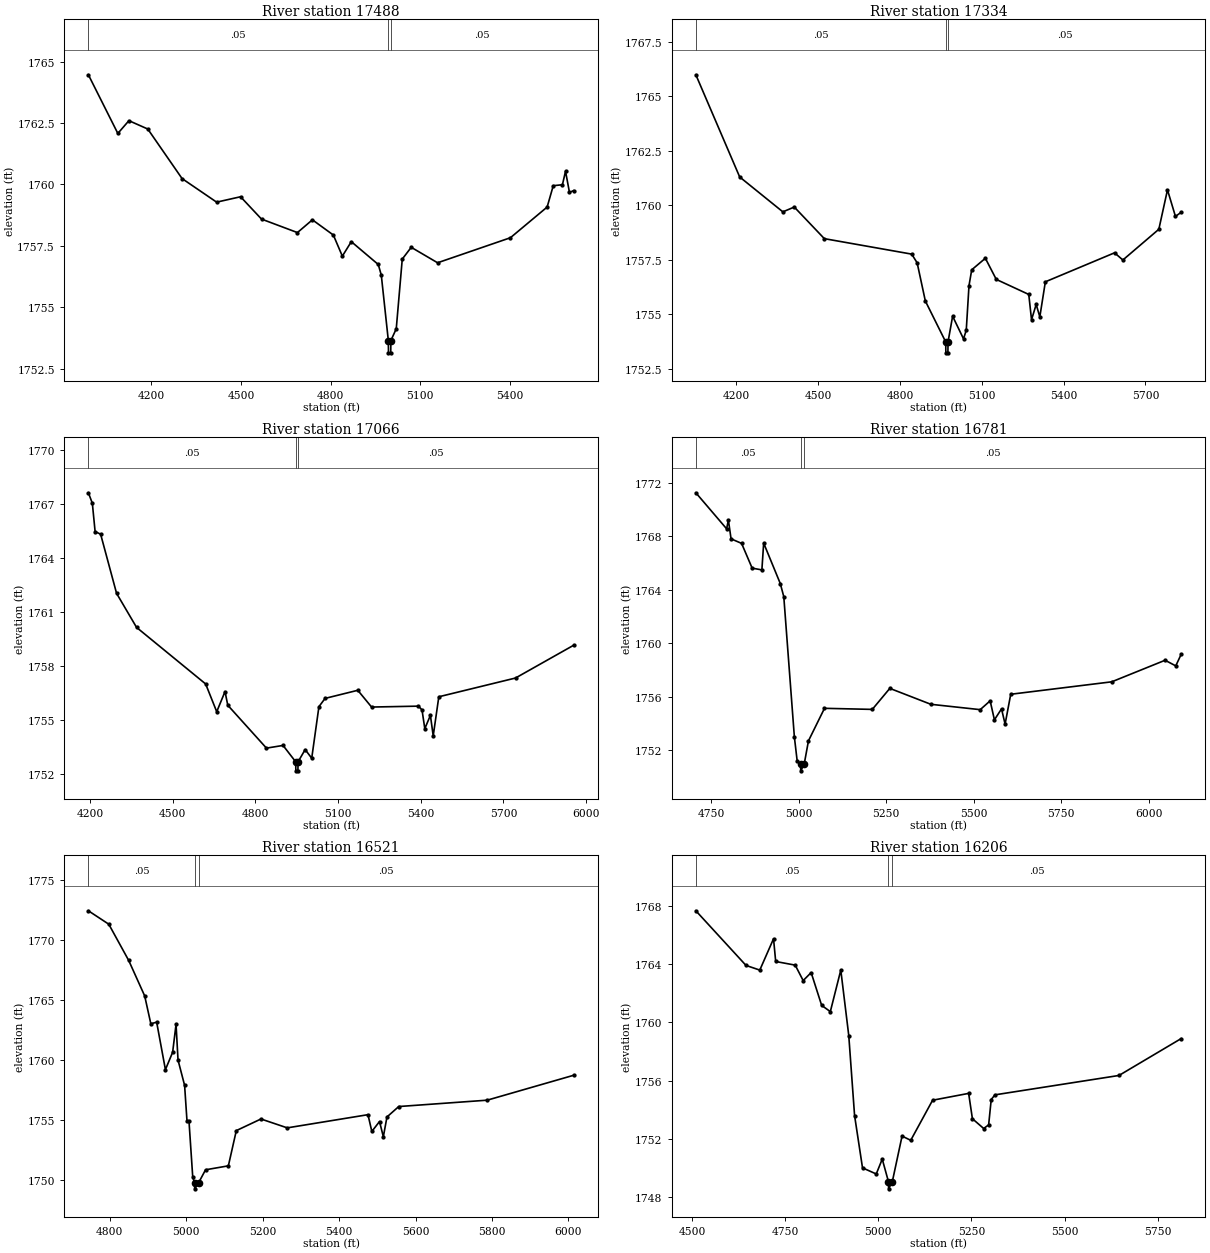
Type RM Length L Ch R = 1 ,17488   ,154,154,154
BEGIN DESCRIPTION:
Elm 02 23 17487.87
END DESCRIPTION:
XS GIS Cut Line= 5
      1616663.49      6846905.15      1615712.94       6846959.4
       1615654.4      6846953.96      1615493.84        6846963.
      1615396.49       6847404.7
#Sta/Elev= 30
  3989.4 1764.47    4088 1762.08  4125.1  1762.6  4188.2 1762.26    4303 1760.24
  4418.6 1759.28  4498.7  1759.5  4568.8 1758.59    4689 1758.04  4739.1 1758.56
  4809.2 1757.94  4839.3 1757.08  4869.3 1757.67  4959.5 1756.74  4969.6 1756.31
  4993.2 1753.64  4993.7 1753.14  5001.2 1753.14  5001.7 1753.64  5019.7 1754.12
  5039.8 1756.96  5069.8 1757.44    5158 1756.81  5401.7 1757.83  5524.6 1759.08
  5545.1 1759.95  5575.8 1759.99  5586.1 1760.54  5599.3 1759.68  5613.4 1759.75
#Mann= 3 ,-1 , 0
  3989.4     .05       0  4993.2     .05       0  5001.7     .05       0
Bank Sta=4993.2,5001.7
XS Rating Curve= 0 ,0
Exp/Cntr=0.3,0.1

Type RM Length L Ch R = 1 ,17334   ,268,268,268
BEGIN DESCRIPTION:
Elm 02 23 17334.25
END DESCRIPTION:
XS GIS Cut Line= 4
      1616665.62       6846792.3       1615719.5      6846823.75
      1615480.74      6846823.75      1615380.92      6847408.58
#Sta/Elev= 30
    4052 1765.98  4212.7 1761.29  4370.9 1759.69  4412.8 1759.91  4522.9 1758.46
  4843.1 1757.75  4863.1 1757.35  4893.1  1755.6  4967.8 1753.72  4968.3 1753.22
  4975.8 1753.22  4976.3 1753.72  4993.1  1754.9  5033.1 1753.86  5043.1 1754.26
  5053.1  1756.3  5063.1 1757.03  5113.1 1757.56  5153.1 1756.59  5272.2  1755.9
  5282.3 1754.74  5299.4 1755.44  5312.7 1754.87    5333 1756.48  5586.6 1757.81
  5617.1 1757.48  5748.9 1758.89  5780.6  1760.7  5809.8 1759.48  5830.7 1759.67
#Mann= 3 ,-1 , 0
    4052     .05       0  4967.8     .03       0  4976.3     .05       0
Bank Sta=4967.8,4976.3
XS Rating Curve= 0 ,0
Exp/Cntr=0.3,0.1

Type RM Length L Ch R = 1 ,17066   ,285,285,285
BEGIN DESCRIPTION:
Elm 02 23 17067.32
END DESCRIPTION:
XS GIS Cut Line= 5
      1616509.35      6846525.38      1615701.27      6846584.17
      1615565.61      6846625.97      1615467.72      6846803.15
      1615363.55      6847399.94
#Sta/Elev= 30
  4194.2 1767.62  4208.6 1767.04  4218.6 1765.47  4238.7 1765.32  4296.5 1762.04
    4369 1760.15  4619.7 1757.01  4659.8 1755.47  4689.9 1756.59  4699.9 1755.83
  4840.2 1753.45  4900.4  1753.6  4946.3 1752.69  4946.8 1752.19  4954.3 1752.19
  4954.8 1752.69  4980.6 1753.37  5004.4 1752.89  5030.5 1755.75  5052.8 1756.21
  5171.5 1756.66  5221.5 1755.73  5391.5 1755.78  5404.5 1755.57  5414.6 1754.53
  5434.9 1755.27  5445.1 1754.13  5465.4  1756.3  5743.6 1757.34  5954.6 1759.16
#Mann= 3 ,-1 , 0
  4194.2     .05       0  4946.3     .03       0  4954.8     .05       0
Bank Sta=4946.3,4954.8
XS Rating Curve= 0 ,0
Exp/Cntr=0.3,0.1

Type RM Length L Ch R = 1 ,16781   ,260,260,260
BEGIN DESCRIPTION:
Elm 02 23 16780.65
END DESCRIPTION:
XS GIS Cut Line= 5
      1615571.06       6846047.9      1615600.58      6846344.79
      1615567.08      6846562.53       1615454.7      6846777.11
      1615344.07      6847393.17
#Sta/Elev= 30
  4705.9 1771.25  4793.8 1768.56  4798.9 1769.21  4806.5 1767.81  4836.6 1767.47
  4866.8 1765.62  4894.6 1765.49  4899.7 1767.49  4947.2 1764.47  4957.2 1763.49
  4987.4 1753.02  4995.4 1751.23  5005.1 1750.98  5005.6 1750.48  5015.5 1750.98
  5027.7 1752.72  5073.5 1755.15  5210.1 1755.07  5260.2 1756.64  5377.5 1755.45
  5518.5 1755.05  5546.9 1755.71  5559.1 1754.29  5579.4 1755.11  5589.6 1753.97
  5605.7  1756.2  5894.4 1757.13  6046.8 1758.74  6077.3 1758.32  6092.7 1759.18
#Mann= 3 ,-1 , 0
  4705.9     .05       0  5005.1     .05       0  5015.5     .05       0
Bank Sta=5005.1,5015.5
XS Rating Curve= 0 ,0
Exp/Cntr=0.3,0.1

Type RM Length L Ch R = 1 ,16521   ,315,315,315
BEGIN DESCRIPTION:
Elm 02 23 16520.68
END DESCRIPTION:
XS GIS Cut Line= 4
      1615282.87      6846146.87      1615357.52      6846395.14
      1615414.08      6846590.93      1615328.86      6847393.17
#Sta/Elev= 30
  4743.8 1772.46  4797.2 1771.34  4849.4 1768.31  4891.2 1765.35  4907.2 1763.03
  4922.5 1763.16  4945.4  1759.2  4964.3 1760.65  4973.2 1762.98  4978.4    1760
  4995.6 1757.89  5001.9 1754.89  5007.1 1754.89  5016.8 1750.27  5021.6 1749.75
  5022.1 1749.25  5032.1 1749.75  5050.4 1750.84  5110.1 1751.17  5130.9 1754.11
  5195.4 1755.08  5264.2 1754.34  5475.4 1755.44  5485.5 1754.04  5505.6 1754.87
  5515.6  1753.6  5525.1 1755.25  5555.9 1756.12  5787.2 1756.65  6013.6 1758.73
#Mann= 3 ,-1 , 0
  4743.8     .05       0  5021.6     .05       0  5032.1     .05       0
Bank Sta=5021.6,5032.1
XS Rating Curve= 0 ,0
Exp/Cntr=0.3,0.1

Type RM Length L Ch R = 1 ,16206   ,267,267,267
BEGIN DESCRIPTION:
Elm 02 23 16205.9
END DESCRIPTION:
XS GIS Cut Line= 4
      1614909.98      6846208.51      1615163.08      6846629.51
      1615219.46        6846757.      1615309.25      6847423.45
#Sta/Elev= 30
    4510 1767.65  4644.7  1763.9  4681.7 1763.58  4718.6 1765.73  4724.4 1764.17
  4776.8 1763.92  4798.2 1762.86  4819.6 1763.41  4847.8 1761.16  4871.1 1760.73
  4899.2 1763.58  4920.6 1759.09  4936.2  1753.6  4957.5 1750.01  4994.4 1749.59
  5010.5 1750.61  5027.1 1749.07  5027.6 1748.57  5037.6 1749.07  5063.7 1752.19
    5087  1751.9  5145.7 1754.65  5242.5 1755.12  5252.6 1753.38  5282.9 1752.71
  5296.2 1752.96  5303.1  1754.7  5313.2 1755.02  5646.2 1756.35  5813.1 1758.88
#Mann= 3 ,-1 , 0
    4510     .05       0  5027.1     .05       0  5037.6     .05       0
Bank Sta=5027.1,5037.6
XS Rating Curve= 0 ,0
Exp/Cntr=0.3,0.1

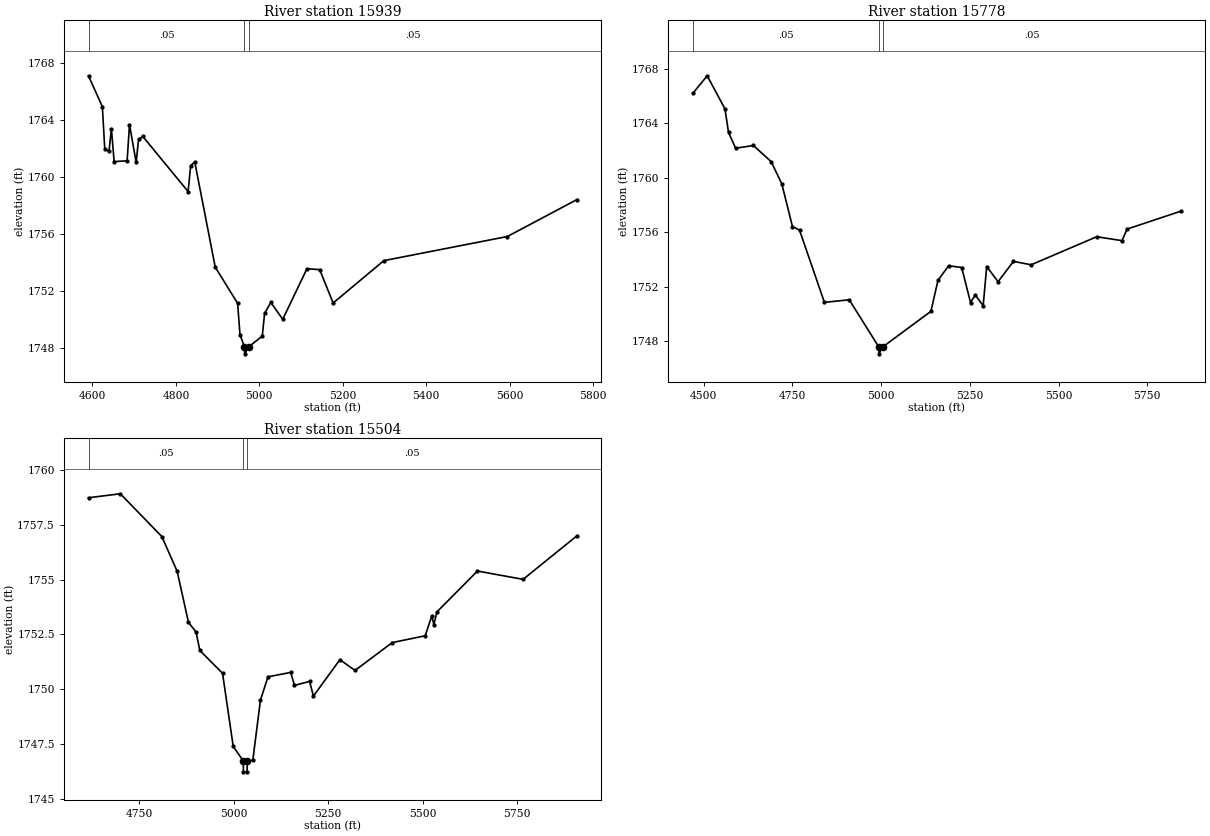
Type RM Length L Ch R = 1 ,15939   ,161,161,161
BEGIN DESCRIPTION:
Elm 02 23 15938.91
END DESCRIPTION:
XS GIS Cut Line= 4
      1614581.45      6846556.58      1614940.85      6846757.99
      1615035.86      6846822.68      1615265.73      6847423.38
#Sta/Elev= 30
  4590.6 1767.08  4623.8 1764.91  4629.5 1761.97  4639.7 1761.78  4645.4 1763.37
    4652 1761.07  4683.1 1761.12  4688.8 1763.66  4704.8 1761.01  4710.5 1762.62
  4720.7 1762.83  4829.2 1758.97  4835.4 1760.79  4845.2 1761.04  4894.3 1753.67
  4947.9 1751.14  4953.6 1748.93  4964.3  1748.1  4964.8  1747.6  4974.9  1748.1
    5007 1748.84  5012.6 1750.44  5027.5  1751.2    5056 1750.02    5114 1753.56
  5144.6  1753.5  5176.8 1751.16  5298.4 1754.13  5594.3 1755.82  5760.7  1758.4
#Mann= 3 ,-1 , 0
  4590.6     .05       0  4964.3     .05       0  4974.9     .05       0
Bank Sta=4964.3,4974.9
XS Rating Curve= 0 ,0
Exp/Cntr=0.3,0.1

Type RM Length L Ch R = 1 ,15778   ,274,274,274
BEGIN DESCRIPTION:
Elm 02 23 15777.52
END DESCRIPTION:
XS GIS Cut Line= 4
      1614274.22       6846825.7      1614807.17      6846837.85
      1615014.18      6846835.67      1615237.69      6847430.34
#Sta/Elev= 30
  4469.5 1766.18  4510.3 1767.48  4560.3 1765.05  4570.3 1763.32  4590.3 1762.16
  4640.3 1762.36  4690.3 1761.18  4720.3 1759.55  4750.4 1756.41  4770.4 1756.14
  4840.4 1750.84  4910.4 1751.03  4993.7 1747.56  4994.2 1747.06  5004.3 1747.56
  5140.4 1750.18  5160.4 1752.46  5190.4 1753.53  5227.1  1753.4    5252 1750.83
  5265.5 1751.38  5287.6 1750.59  5297.6 1753.47  5329.6 1752.36    5373 1753.85
  5422.8  1753.6  5607.4 1755.66  5678.9 1755.37  5692.8 1756.22  5844.9 1757.54
#Mann= 3 ,-1 , 0
  4469.5     .05       0  4993.7     .03       0  5004.3     .05       0
Bank Sta=4993.7,5004.3
XS Rating Curve= 0 ,0
Exp/Cntr=0.3,0.1

Type RM Length L Ch R = 1 ,15504   ,371,371,371
BEGIN DESCRIPTION:
Elm 02 23 15504.43
END DESCRIPTION:
XS GIS Cut Line= 4
       1614190.9      6846957.64      1614576.27      6846968.06
      1614996.78      6846973.52      1615198.12      6847414.03
#Sta/Elev= 30
  4616.8 1758.73  4700.9 1758.91  4810.6 1756.96    4851 1755.38    4881 1753.05
    4901 1752.61    4911 1751.77    4971 1750.73  4999.2  1747.4  5025.7 1746.74
  5026.2 1746.24  5035.9 1746.24  5036.4 1746.74    5051 1746.77  5071.1  1749.5
  5091.1 1750.57  5151.1 1750.77  5161.1 1750.18  5201.1 1750.36  5211.1 1749.69
  5281.1 1751.35  5321.1 1750.86  5419.5 1752.13  5506.5 1752.44    5524 1753.34
  5529.5 1752.95  5537.7 1753.53  5644.7 1755.39  5765.3 1755.01  5907.2 1756.99
#Mann= 3 ,-1 , 0
  4616.8     .05       0  5025.7     .03       0  5036.4     .05       0
Bank Sta=5025.7,5036.4
XS Rating Curve= 0 ,0
Exp/Cntr=0.3,0.1