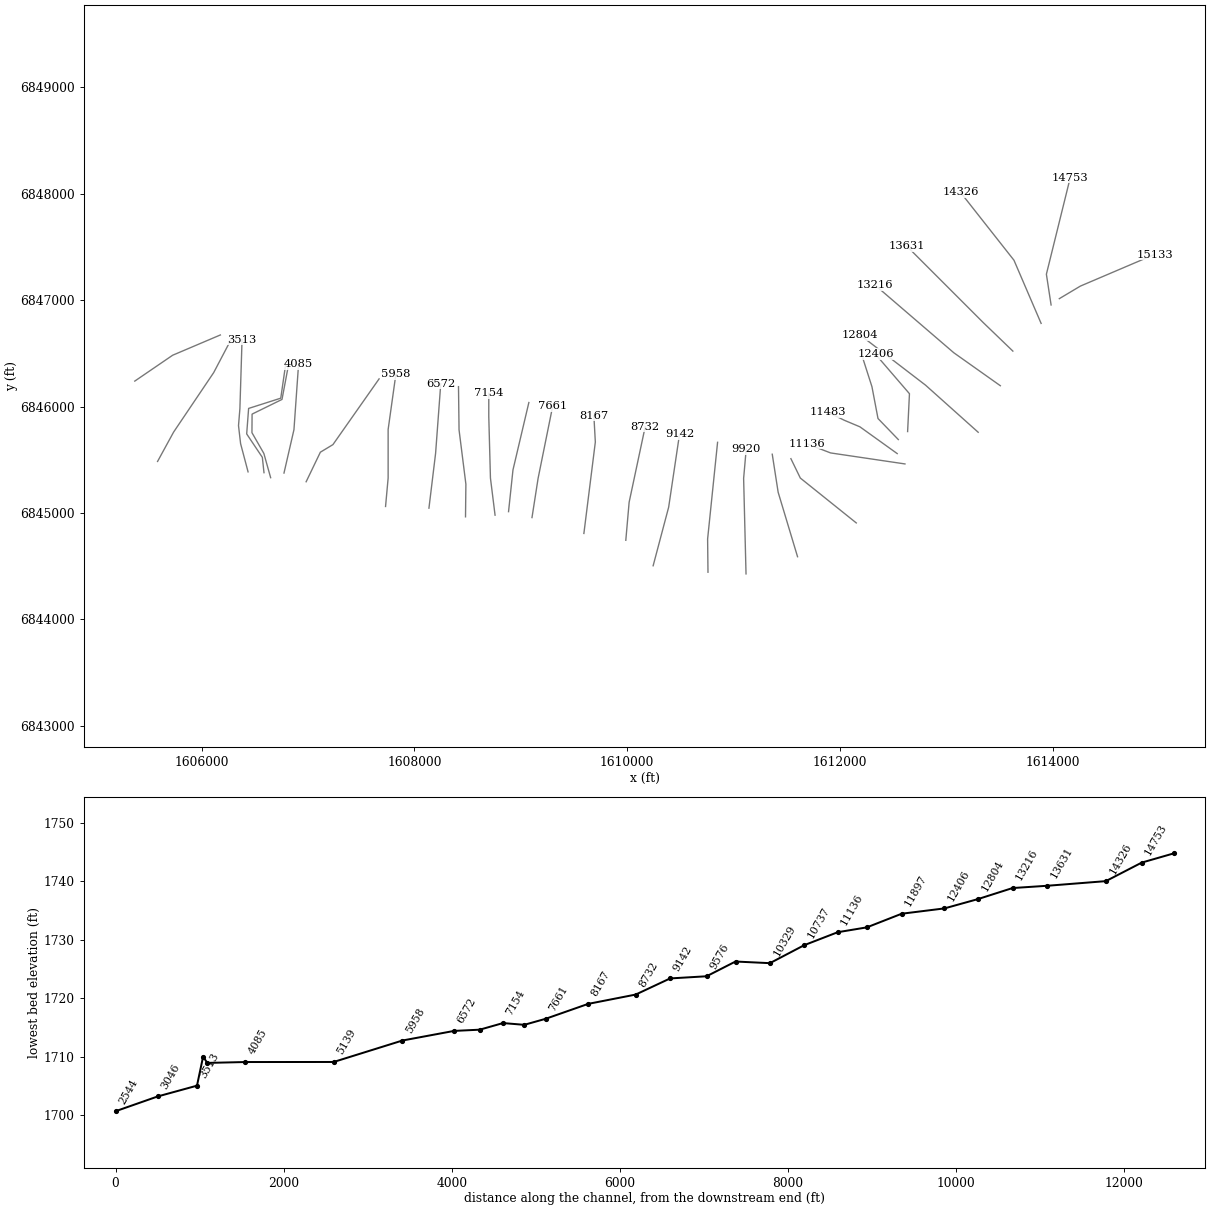
HEC-RAS study Elm 02 23.prj: Elm 02 23 Base Level Engineering

--- Elm 02 23.g01 (geometry) --- (continued)

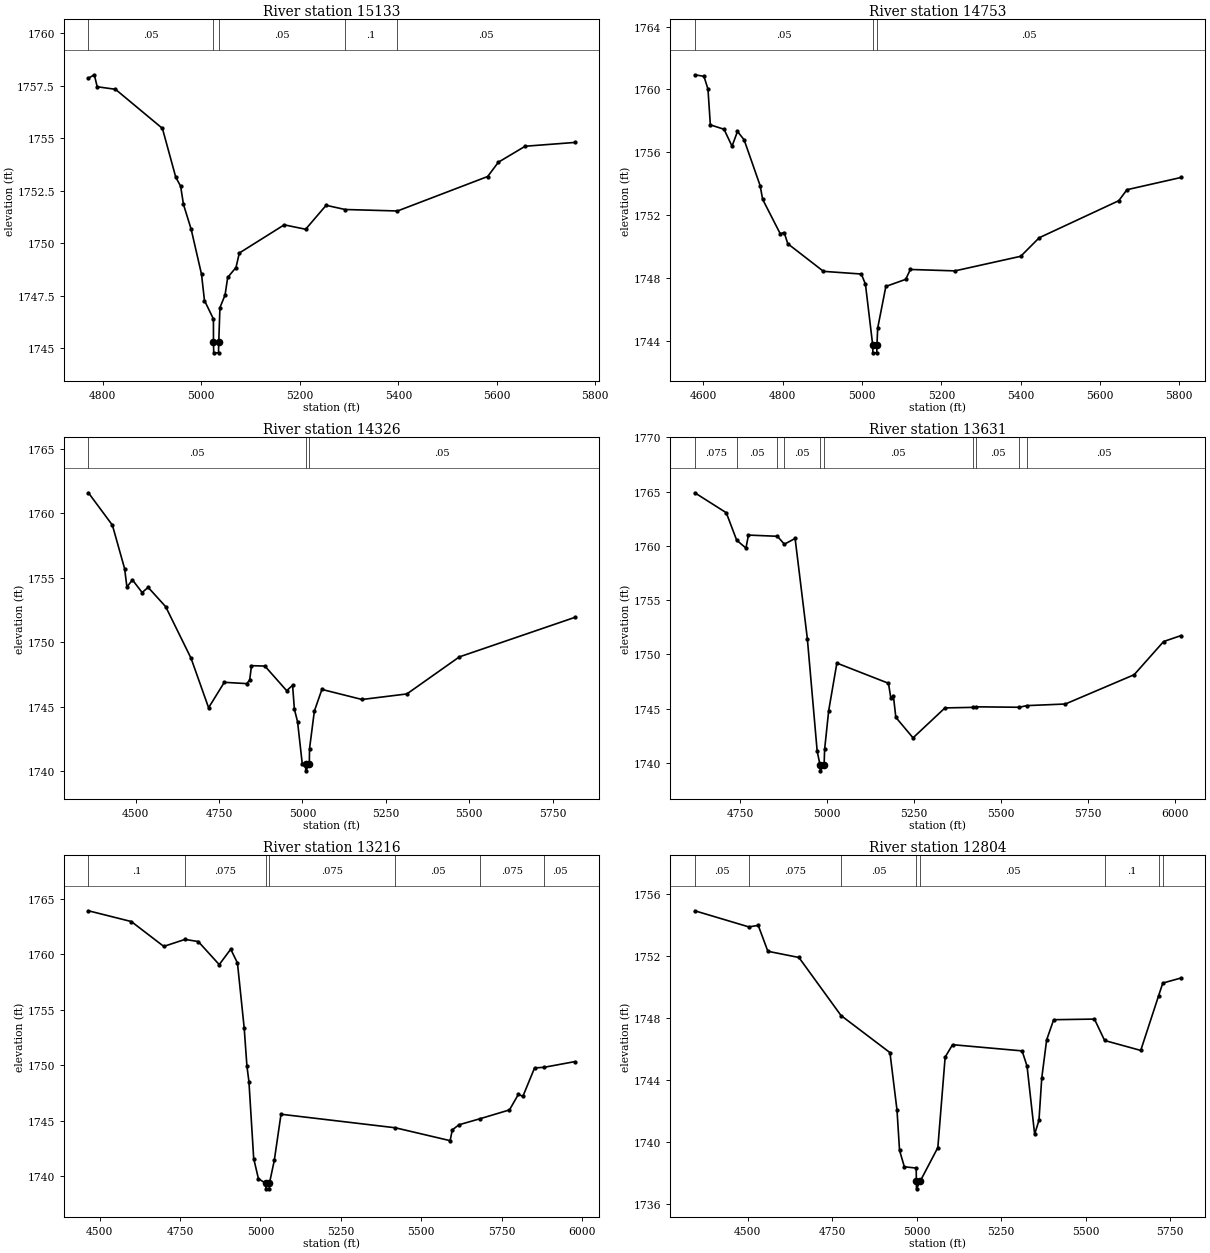
Type RM Length L Ch R = 1 ,15133   ,380,380,380
BEGIN DESCRIPTION:
Elm 02 23 15133.32
END DESCRIPTION:
XS GIS Cut Line= 3
      1614063.44       6847014.6      1614261.34      6847132.64
      1614957.55      6847429.53
#Sta/Elev= 30
  4770.8 1757.86  4782.8 1758.02  4788.6 1757.45  4825.6 1757.33    4921 1755.47
  4948.2 1753.14    4958 1752.72  4963.8 1751.85  4979.4 1750.67  5000.4 1748.53
  5006.4 1747.28  5024.6  1746.4  5024.7 1745.29  5025.2 1744.79  5034.9 1744.79
  5035.4 1745.29  5037.8 1746.94  5048.2 1747.54  5053.6 1748.38  5070.4 1748.85
  5077.2 1749.54  5168.3 1750.88  5211.8 1750.67  5253.4 1751.81  5291.9 1751.61
  5398.3 1751.54  5581.4 1753.18  5603.1 1753.86  5657.5 1754.62  5758.1  1754.8
#Mann= 5 ,-1 , 0
  4770.8     .05       0  5024.7     .04       0  5035.4     .05       0
  5291.9      .1       0  5398.3     .05       0
Bank Sta=5024.7,5035.4
XS Rating Curve= 0 ,0
Exp/Cntr=0.3,0.1

Type RM Length L Ch R = 1 ,14753   ,427,427,427
BEGIN DESCRIPTION:
Mapping XS a153f957
END DESCRIPTION:
XS GIS Cut Line= 3
      1613986.07      6846955.17      1613941.79      6847244.26
      1614165.76      6848150.53
#Sta/Elev= 30
  4578.4 1760.93  4601.5 1760.83  4611.6 1760.02  4617.6 1757.74  4652.1 1757.46
  4672.3 1756.38    4686 1757.32  4702.7 1756.79  4743.1 1753.87  4749.4    1753
  4793.7 1750.81  4803.8 1750.88  4812.8 1750.17  4902.8 1748.41  4998.3 1748.24
  5008.6 1747.59  5026.9 1743.72  5027.4 1743.22  5037.1 1743.22  5037.6 1743.72
  5039.5  1744.8  5060.1 1747.45    5110  1747.9  5121.9 1748.53  5234.3 1748.44
  5400.1 1749.37  5446.7 1750.55  5647.3 1752.91  5667.9 1753.61  5804.4 1754.39
#Mann= 3 ,-1 , 0
  4578.4     .05       0  5026.9     .06       0  5037.6     .05       0
Bank Sta=5026.9,5037.6
XS Rating Curve= 0 ,0
Exp/Cntr=0.3,0.1

Type RM Length L Ch R = 1 ,14326   ,695,695,695
BEGIN DESCRIPTION:
Elm 02 23 14325.77
END DESCRIPTION:
XS GIS Cut Line= 3
      1613892.25      6846781.93      1613637.03       6847375.7
      1613134.74      6848013.33
#Sta/Elev= 30
  4358.2  1761.6  4430.1 1759.09  4466.7 1755.72  4473.6  1754.3  4490.2 1754.85
  4519.2 1753.87  4537.3 1754.27  4589.9 1752.77    4666 1748.77  4718.5 1744.94
  4765.6 1746.91  4832.8 1746.81  4841.7 1747.09  4847.1  1748.2  4887.3 1748.17
  4952.6 1746.26  4970.3 1746.68  4975.7 1744.83  4985.2 1743.86  4999.3  1740.6
  5009.3 1740.55  5009.8 1740.05  5020.4 1740.55  5021.2 1741.78  5035.6 1744.68
  5058.2 1746.36  5178.4 1745.58    5313 1746.01  5470.2 1748.88  5816.2 1751.94
#Mann= 3 ,-1 , 0
  4358.2     .05       0  5009.3     .05       0  5020.4     .05       0
Bank Sta=5009.3,5020.4
XS Rating Curve= 0 ,0
Exp/Cntr=0.3,0.1

Type RM Length L Ch R = 1 ,13631   ,415,415,415
BEGIN DESCRIPTION:
Elm 02 23 13631.37
END DESCRIPTION:
XS GIS Cut Line= 3
      1613626.63      6846521.52      1613347.97      6846789.76
      1612631.81      6847505.93
#Sta/Elev= 30
  4619.3 1764.89  4709.9 1763.05  4739.8 1760.52  4766.5 1759.79  4773.7 1760.99
    4857 1760.88  4877.1 1760.15    4908 1760.68  4943.2 1751.45  4971.5 1741.07
    4980 1739.76  4980.5 1739.26  4991.4 1739.76  4992.9 1741.23  5004.7 1744.82
  5028.2 1749.19  5176.7 1747.33  5183.7 1745.93  5190.8 1746.19  5197.9 1744.19
  5247.4  1742.3  5339.3 1745.06  5418.8 1745.11    5430 1745.16  5553.6 1745.12
  5574.1 1745.27  5685.8 1745.42  5883.8 1748.12  5968.6 1751.18  6018.9 1751.73
#Mann= 10 ,-1 , 0
  4619.3    .075       0  4739.8     .05       0    4857    .075       0
  4877.1     .05       0    4980     .03       0  4991.4     .05       0
  5418.8    .075       0    5430     .05       0  5553.6    .075       0
  5574.1     .05       0
Bank Sta=4980,4991.4
XS Rating Curve= 0 ,0
Exp/Cntr=0.3,0.1

Type RM Length L Ch R = 1 ,13216   ,412,412,412
BEGIN DESCRIPTION:
Elm 02 23 13216.36
END DESCRIPTION:
XS GIS Cut Line= 3
      1613508.89      6846196.03      1613071.41       6846505.9
       1612331.8      6847141.34
#Sta/Elev= 30
  4465.4 1763.92  4598.7 1762.95  4699.6 1760.71  4765.4 1761.34  4806.7 1761.15
  4871.9 1759.07  4907.6 1760.46  4928.5 1759.22  4949.4 1753.38    4958 1749.92
  4964.2 1748.53    4979  1741.6  4993.7 1739.78  5016.4 1739.37  5016.9 1738.87
  5027.4 1738.87  5027.9 1739.37    5043 1741.43  5063.9 1745.59  5419.3 1744.37
  5589.5 1743.21  5596.1 1744.18  5616.9 1744.64  5682.8 1745.19  5773.8 1745.98
  5801.3 1747.37  5815.6 1747.21  5851.8 1749.76  5881.7 1749.82  5976.6 1750.33
#Mann= 7 ,-1 , 0
  4465.4      .1       0  4765.4    .075       0  5016.4     .07       0
  5027.9    .075       0  5419.3     .05       0  5682.8    .075       0
  5881.7     .05       0
Bank Sta=5016.4,5027.9
XS Rating Curve= 0 ,0
Exp/Cntr=0.3,0.1

Type RM Length L Ch R = 1 ,12804   ,398,398,398
BEGIN DESCRIPTION:
Elm 02 23 12803.88
END DESCRIPTION:
XS GIS Cut Line= 3
      1613300.56      6845758.52      1612805.78      6846201.22
      1612191.23      6846672.55
#Sta/Elev= 30
    4344  1754.9    4504 1753.86  4531.6 1753.96  4560.1 1752.29    4652 1751.89
  4776.5 1748.15  4921.2 1745.76  4942.1 1742.05  4949.6 1739.46  4963.8  1738.4
  4998.9 1738.32  4999.3 1737.48  4999.8 1736.98  5010.9 1737.48  5062.9 1739.64
  5084.5 1745.47  5106.4 1746.27  5312.1 1745.87  5326.7 1744.89  5349.2  1740.5
    5362  1741.4  5370.2 1744.11  5384.7 1746.58  5405.5 1747.88  5526.1 1747.92
  5556.2 1746.54    5663  1745.9  5715.8 1749.42  5728.2 1750.24  5782.4 1750.57
#Mann= 8 ,-1 , 0
    4344     .05       0    4504    .075       0  4776.5     .05       0
  4999.3     .03       0  5010.9     .05       0  5556.2      .1       0
  5715.8    .075       0  5728.2      .1       0
Bank Sta=4999.3,5010.9
XS Rating Curve= 0 ,0
Exp/Cntr=0.3,0.1

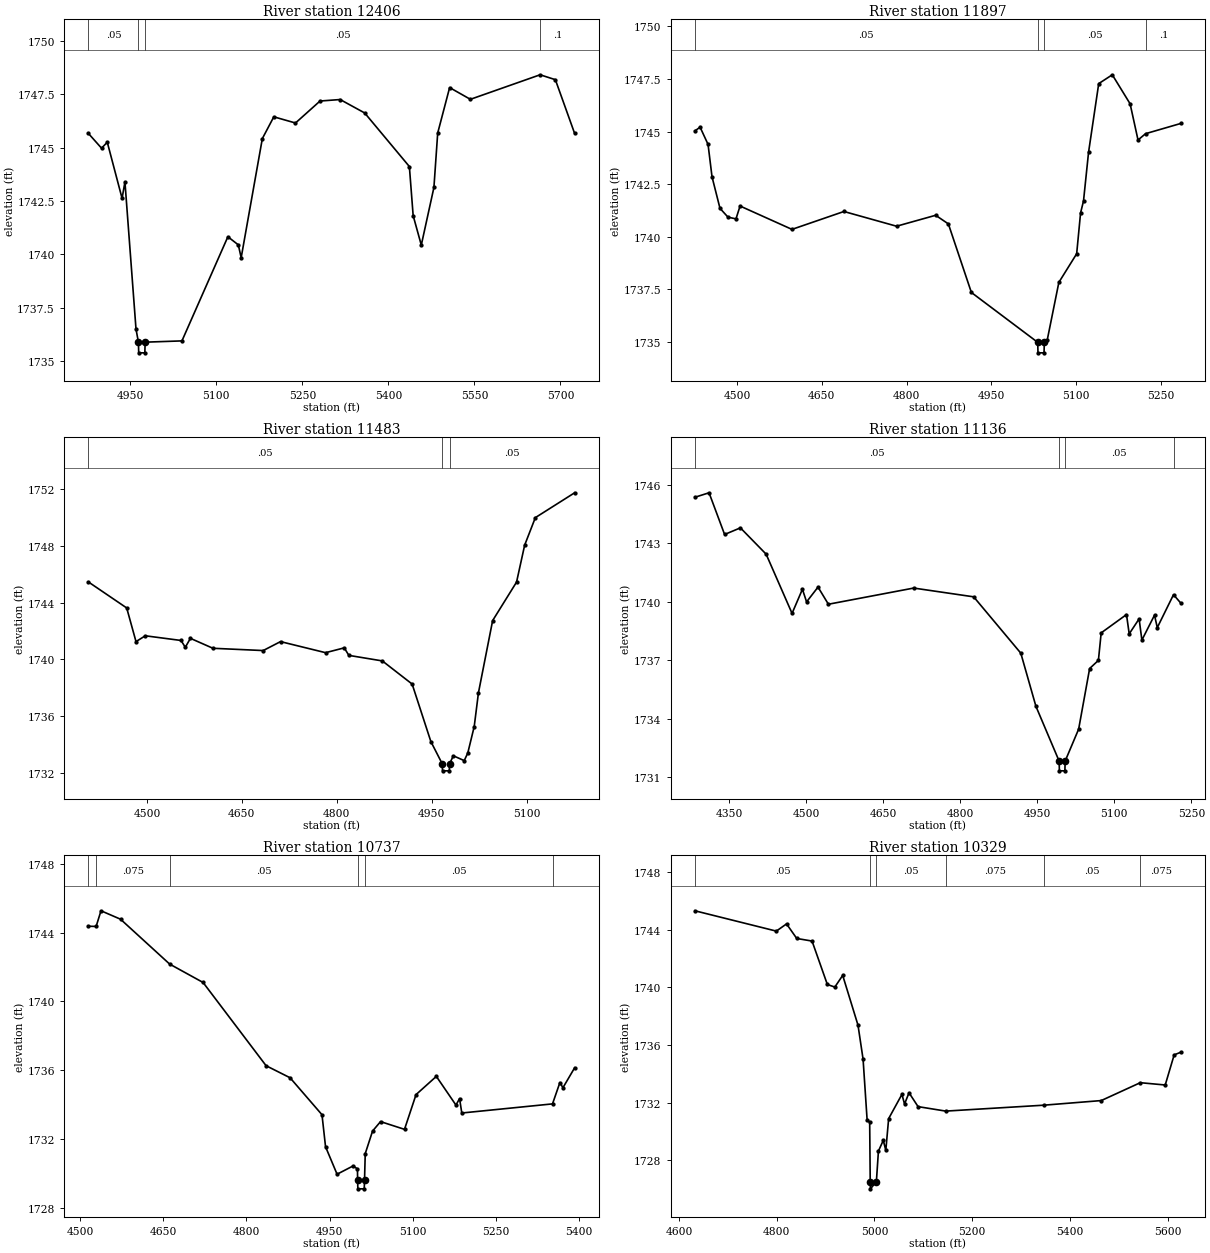
Type RM Length L Ch R = 1 ,12406   ,509,509,509
BEGIN DESCRIPTION:
Elm 02 23 12376.19
END DESCRIPTION:
XS GIS Cut Line= 3
      1612637.11      6845765.09      1612654.47      6846120.99
      1612333.84      6846493.61
#Sta/Elev= 30
  4876.9 1745.67  4899.8 1744.98  4909.8 1745.26  4935.6 1742.63  4940.6  1743.4
  4959.9  1736.5  4964.1 1735.89  4964.6 1735.39  4975.3 1735.39  4975.8 1735.89
    5040 1735.95  5120.1 1740.83  5138.3 1740.45  5143.3 1739.85  5180.2 1745.43
  5200.2 1746.45    5238 1746.16  5280.8 1747.19  5315.9 1747.26  5358.7 1746.63
  5436.6 1744.12  5443.2 1741.82  5457.4 1740.44  5479.4 1743.14    5486 1745.69
  5506.8 1747.82    5543 1747.27  5664.6 1748.42  5691.2 1748.19  5724.8 1745.67
#Mann= 4 ,-1 , 0
  4876.9     .05       0  4964.1     .05       0  4975.8     .05       0
  5664.6      .1       0
Bank Sta=4964.1,4975.8
XS Rating Curve= 0 ,0
Exp/Cntr=0.3,0.1

Type RM Length L Ch R = 1 ,11897   ,414,414,414
BEGIN DESCRIPTION:
Elm 02 23 11897.48
END DESCRIPTION:
XS GIS Cut Line= 4
      1612549.73       6845689.9       1612358.7      6845887.77
      1612301.88      6846186.58      1612216.24      6846453.89
#Sta/Elev= 30
  4425.6 1745.03  4434.8 1745.21  4448.9 1744.39  4455.9 1742.85    4470 1741.35
  4484.2 1740.93  4498.3 1740.85  4505.5 1741.46  4597.3 1740.35  4689.2  1741.2
  4782.3  1740.5  4851.4 1741.02  4873.9 1740.61  4914.6 1737.35  5031.9 1734.98
  5032.4 1734.48  5043.1 1734.48  5043.6 1734.98  5048.6 1735.07  5069.3 1737.83
  5100.8 1739.19  5107.7 1741.13  5112.9  1741.7  5121.8 1744.01  5139.8 1747.28
  5163.8  1747.7  5195.3 1746.32  5209.3  1744.6  5222.7  1744.9  5285.5 1745.39
#Mann= 4 ,-1 , 0
  4425.6     .05       0  5031.9     .05       0  5043.6     .05       0
  5222.7      .1       0
Bank Sta=5031.9,5043.6
XS Rating Curve= 0 ,0
Exp/Cntr=0.3,0.1

Type RM Length L Ch R = 1 ,11483   ,347,347,347
BEGIN DESCRIPTION:
Elm 02 23 11483.17
END DESCRIPTION:
XS GIS Cut Line= 4
      1612539.36      6845557.91      1612188.64      6845809.66
      1612041.46      6845871.47      1611882.59      6845949.61
#Sta/Elev= 30
  4407.6 1745.45  4468.1 1743.62  4482.8 1741.25  4497.5 1741.66    4554 1741.33
  4560.7 1740.85  4568.8 1741.48  4604.4 1740.78  4683.8 1740.62  4711.2 1741.25
  4782.4 1740.47  4811.9 1740.81  4819.2 1740.28  4872.1 1739.89  4919.2 1738.26
  4948.8 1734.21  4966.7 1732.65  4967.2 1732.15  4977.9 1732.15  4978.4 1732.65
  4984.3 1733.21  5001.5 1732.87  5007.1  1733.4  5017.3 1735.27    5024 1737.65
  5046.4 1742.73  5084.2 1745.44    5097 1748.04  5113.9 1749.98    5176 1751.73
#Mann= 3 ,-1 , 0
  4407.6     .05       0  4966.7     .05       0  4978.4     .05       0
Bank Sta=4966.7,4978.4
XS Rating Curve= 0 ,0
Exp/Cntr=0.3,0.1

Type RM Length L Ch R = 1 ,11136   ,399,399,399
BEGIN DESCRIPTION:
Elm 02 23 11324.734
END DESCRIPTION:
XS GIS Cut Line= 3
      1612612.28       6845460.7      1611913.15      6845564.14
      1611688.72      6845650.45
#Sta/Elev= 30
  4282.9 1745.36  4310.5 1745.59  4340.8 1743.45  4371.6 1743.79  4421.7 1742.44
  4472.2  1739.4  4492.4 1740.64  4500.5 1739.99  4522.8 1740.75    4543 1739.87
  4709.2  1740.7    4826 1740.25  4917.8 1737.36  4947.3 1734.63  4992.5 1731.82
    4993 1731.32  5003.7 1731.32  5004.2 1731.82  5030.5 1733.46  5051.9 1736.57
    5069 1736.99  5074.4  1738.4  5123.7 1739.34    5129 1738.35  5148.3 1739.12
  5153.7 1738.03  5178.3 1739.31  5183.7 1738.67  5215.3 1740.36  5230.1 1739.91
#Mann= 4 ,-1 , 0
  4282.9     .05       0  4992.5     .03       0  5004.2     .05       0
  5215.3    .075       0
Bank Sta=4992.5,5004.2
XS Rating Curve= 0 ,0
Exp/Cntr=0.3,0.1

Type RM Length L Ch R = 1 ,10737   ,408,408,408
BEGIN DESCRIPTION:
Mapping XS 6575bd0d
END DESCRIPTION:
XS GIS Cut Line= 3
      1612154.44      6844906.17      1611628.43      6845328.02
      1611539.94       6845510.2
#Sta/Elev= 30
    4515 1744.37  4528.9 1744.36  4537.7 1745.27  4572.9 1744.78  4661.5 1742.17
  4721.8  1741.1  4835.4 1736.26  4878.6 1735.56  4936.2 1733.41  4942.6 1731.55
  4963.4 1729.95  4992.2 1730.43  5000.2 1730.26  5000.4  1729.6  5000.9  1729.1
  5012.4  1729.1  5012.9  1729.6  5014.2 1731.15  5027.4 1732.46  5041.8 1733.01
    5085 1732.56  5105.8 1734.58  5142.4 1735.64  5177.8 1733.97  5184.3 1734.35
  5188.3 1733.51  5351.9 1734.04  5365.2 1735.28  5370.7 1734.98  5391.8 1736.14
#Mann= 6 ,-1 , 0
    4515      .1       0  4528.9    .075       0  4661.5     .05       0
  5000.4     .03       0  5012.9     .05       0  5351.9    .075       0
Bank Sta=5000.4,5012.9
XS Rating Curve= 0 ,0
Exp/Cntr=0.3,0.1

Type RM Length L Ch R = 1 ,10329   ,409,409,409
BEGIN DESCRIPTION:
Mapping XS be5c1527
END DESCRIPTION:
XS GIS Cut Line= 3
      1611602.38      6844588.45      1611420.09      6845194.34
      1611364.53      6845552.03
#Sta/Elev= 30
  4632.7 1745.31  4799.3  1743.9  4820.2  1744.4  4841.1 1743.39  4872.4 1743.21
  4903.7  1740.2    4919 1740.02  4935.1 1740.83  4966.4 1737.38  4976.8 1735.02
  4985.1 1730.79  4990.3 1730.65  4991.4 1726.53  4991.9 1726.03    5004 1726.53
  5008.2 1728.65  5018.1 1729.39  5023.3  1728.7  5029.1  1730.9  5056.3 1732.58
  5061.6 1731.91  5070.8 1732.69  5089.3 1731.73  5145.9 1731.42  5346.5 1731.83
    5464 1732.15  5543.9 1733.39  5594.9 1733.23  5613.2 1735.32  5627.4 1735.51
#Mann= 6 ,-1 , 0
  4632.7     .05       0  4991.4     .05       0    5004     .05       0
  5145.9    .075       0  5346.5     .05       0  5543.9    .075       0
Bank Sta=4991.4,5004
XS Rating Curve= 0 ,0
Exp/Cntr=0.3,0.1

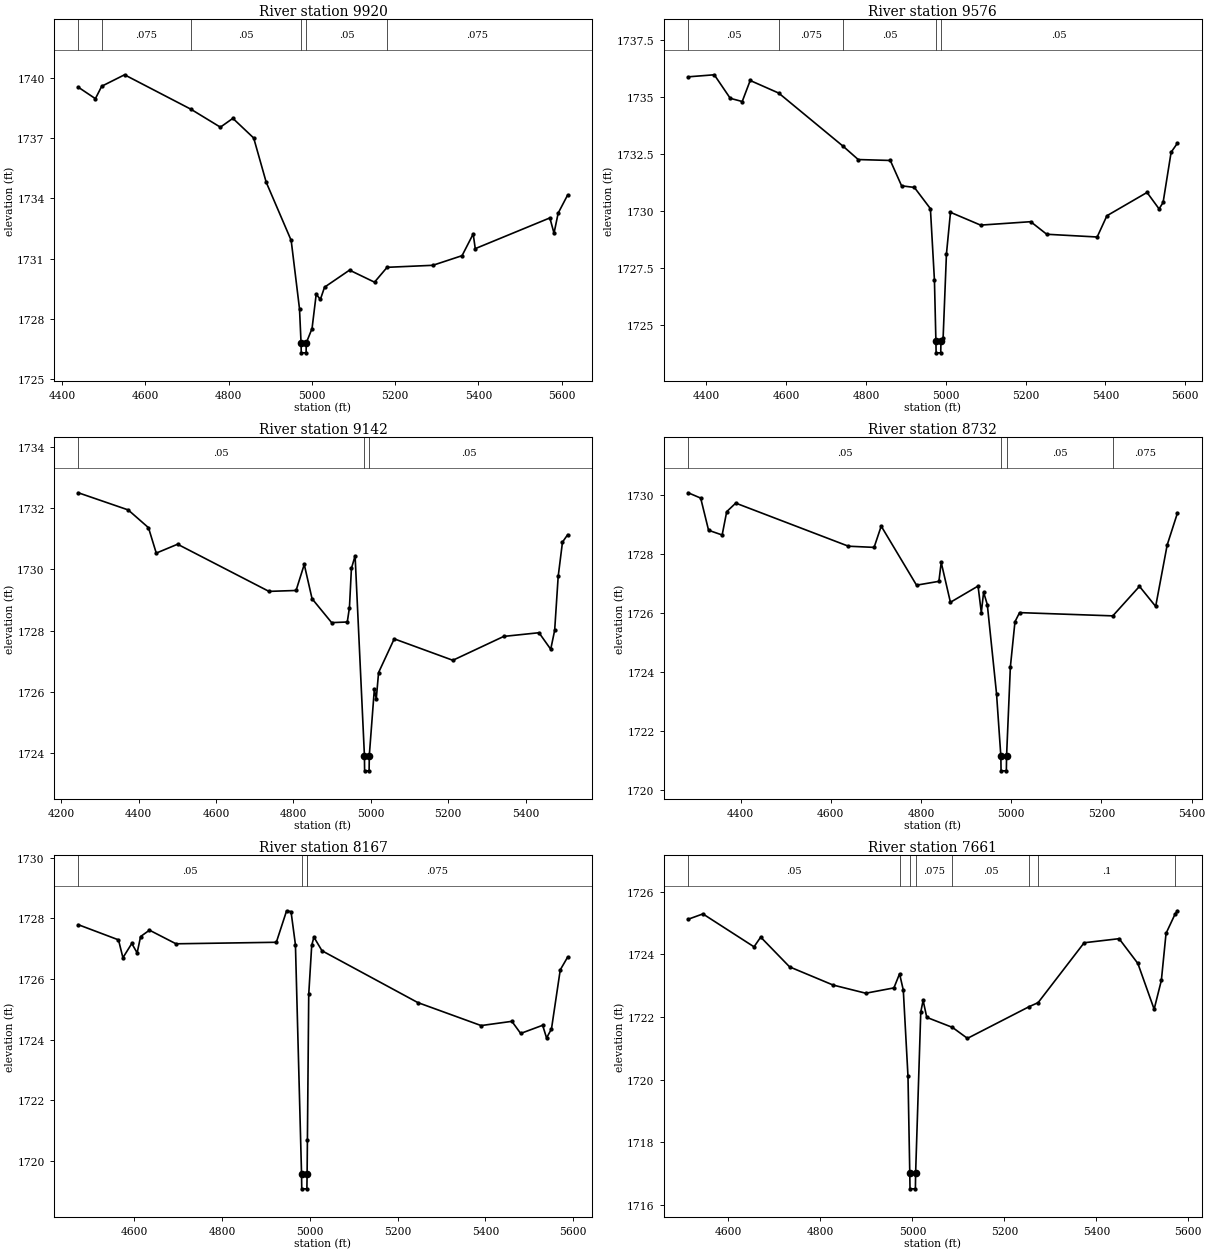
Type RM Length L Ch R = 1 ,9920    ,344,344,344
BEGIN DESCRIPTION:
Mapping XS a8b7af28
END DESCRIPTION:
XS GIS Cut Line= 3
      1611118.01      6844427.02      1611095.44      6845324.55
      1611119.74      6845600.57
#Sta/Elev= 30
  4439.3 1739.54  4480.3 1738.97  4495.5 1739.59  4550.3 1740.16    4710 1738.44
  4780.4 1737.55  4810.4 1737.99  4860.4 1737.01  4890.4 1734.81  4950.4 1731.91
  4970.4  1728.5  4974.1 1726.81  4974.6 1726.31  4986.2 1726.31  4986.7 1726.81
  5000.5 1727.52  5010.5 1729.23  5020.5 1728.97  5030.5 1729.58  5090.5 1730.43
  5150.5 1729.83  5180.7 1730.57  5290.5 1730.67  5360.7 1731.15  5387.4 1732.23
  5392.4  1731.5  5571.5 1733.03  5581.5 1732.27  5591.5 1733.27  5614.2 1734.17
#Mann= 6 ,-1 , 0
  4439.3     .05       0  4495.5    .075       0    4710     .05       0
  4974.1     .05       0  4986.7     .05       0  5180.7    .075       0
Bank Sta=4974.1,4986.7
XS Rating Curve= 0 ,0
Exp/Cntr=0.3,0.1

Type RM Length L Ch R = 1 ,9576    ,434,434,434
BEGIN DESCRIPTION:
Mapping XS baa4f41e
END DESCRIPTION:
XS GIS Cut Line= 3
      1610760.37      6844442.57       1610756.9      6844755.11
      1610850.56      6845663.93
#Sta/Elev= 30
  4354.3 1735.87  4419.7 1735.96  4459.7 1734.93  4489.7 1734.79  4509.7 1735.71
  4581.1 1735.16  4742.7 1732.83  4780.4 1732.25  4860.8 1732.21  4889.1  1731.1
  4921.1 1731.03  4961.3  1730.1  4971.4 1726.97  4975.1 1724.29  4975.6 1723.79
  4987.2 1723.79  4987.7 1724.29  4993.1 1724.42  5001.5 1728.12  5011.6 1729.94
  5087.1 1729.38  5212.6 1729.53  5252.8 1728.98  5379.2 1728.86  5403.6 1729.79
  5504.2 1730.81  5534.3 1730.09  5544.4 1730.37  5564.5 1732.57  5580.5 1732.97
#Mann= 5 ,-1 , 0
  4354.3     .05       0  4581.1    .075       0  4742.7     .05       0
  4975.1     .03       0  4987.7     .05       0
Bank Sta=4975.1,4987.7
XS Rating Curve= 0 ,0
Exp/Cntr=0.3,0.1

Type RM Length L Ch R = 1 ,9142    ,410,410,410
BEGIN DESCRIPTION:
Mapping XS d718593d
END DESCRIPTION:
XS GIS Cut Line= 3
      1610244.74      6844503.36      1610390.58      6845053.72
        1610493.      6845741.18
#Sta/Elev= 30
  4244.4  1732.5  4373.3 1731.94  4425.7 1731.36  4445.8 1730.53  4500.9 1730.82
    4737 1729.28  4807.1 1729.31  4828.2 1730.16  4848.4 1729.04    4899 1728.26
  4939.4 1728.28    4945 1728.75  4950.1 1730.03  4959.6 1730.44  4983.7 1723.92
  4984.2 1723.42  4995.8 1723.42  4996.3 1723.92  5009.3 1726.08  5014.3 1725.77
  5020.3 1726.63  5060.7 1727.73  5212.2 1727.03  5343.8 1727.81  5434.8 1727.93
  5465.1 1727.39  5475.3 1728.01  5484.4 1729.77  5495.5 1730.89  5508.8 1731.13
#Mann= 3 ,-1 , 0
  4244.4     .05       0  4983.7     .05       0  4996.3     .05       0
Bank Sta=4983.7,4996.3
XS Rating Curve= 0 ,0
Exp/Cntr=0.3,0.1

Type RM Length L Ch R = 1 ,8732    ,565,565,565
BEGIN DESCRIPTION:
Mapping XS 2d2111f1
END DESCRIPTION:
XS GIS Cut Line= 3
       1609987.8      6844742.96      1610019.05      6845100.59
      1610170.04      6845810.41
#Sta/Elev= 30
  4283.8 1730.08  4311.5  1729.9    4329 1728.81  4359.1 1728.65  4369.2 1729.44
  4389.2 1729.73    4639 1728.27  4695.9 1728.23  4711.7 1728.95    4790 1726.95
  4839.6 1727.08  4844.7 1727.72  4865.1 1726.37  4926.4 1726.92  4933.6 1726.02
  4938.7 1726.71  4946.9 1726.29  4967.3 1723.28  4976.9 1721.16  4977.4 1720.66
  4989.1 1720.66  4989.6 1721.16    4998 1724.18  5008.2 1725.71  5018.4 1726.02
  5225.1 1725.91  5284.2 1726.91  5320.1 1726.23  5345.6 1728.31  5368.5  1729.4
#Mann= 4 ,-1 , 0
  4283.8     .05       0  4976.9     .05       0  4989.6     .05       0
  5225.1    .075       0
Bank Sta=4976.9,4989.6
XS Rating Curve= 0 ,0
Exp/Cntr=0.3,0.1

Type RM Length L Ch R = 1 ,8167    ,506,506,506
BEGIN DESCRIPTION:
Mapping XS 9f2148b1
END DESCRIPTION:
XS GIS Cut Line= 3
       1609593.7      6844807.19      1609701.34      6845666.57
      1609687.55      6845914.79
#Sta/Elev= 30
  4472.5 1727.79    4564 1727.29  4574.1  1726.7  4594.3 1727.17  4606.5 1726.86
  4614.4  1727.4  4634.6 1727.61    4695 1727.16  4923.6 1727.21    4947 1728.25
  4957.1 1728.22  4967.1 1727.13    4981 1719.57  4981.5 1719.07  4993.2 1719.07
  4993.7 1719.57  4994.4 1720.69  4997.4 1725.49  5004.2 1727.11  5009.2 1727.38
  5027.6 1726.93  5245.8 1725.22  5390.1 1724.46  5460.2  1724.6  5480.2  1724.2
  5530.3 1724.47  5539.2 1724.05  5550.4 1724.35  5570.4  1726.3  5587.2 1726.72
#Mann= 4 ,-1 , 0
  4472.5     .05       0    4981     .07       0  4993.7     .05       0
  4994.4    .075       0
Bank Sta=4981,4993.7
XS Rating Curve= 0 ,0
Exp/Cntr=0.3,0.1

Type RM Length L Ch R = 1 ,7661    ,254,254,254
BEGIN DESCRIPTION:
Mapping XS 554adbdd
END DESCRIPTION:
XS GIS Cut Line= 3
      1609105.85      6844956.48      1609163.15      6845324.55
      1609300.12      6846002.45
#Sta/Elev= 30
  4512.4 1725.12  4544.4 1725.29  4655.6 1724.24  4670.1 1724.55    4733  1723.6
  4827.7 1723.02  4898.6 1722.76  4959.8 1722.93  4972.1 1723.38  4980.2 1722.86
  4990.4 1720.11  4994.3 1717.02  4994.8 1716.52  5006.5 1716.52    5007 1717.02
  5018.2 1722.16  5023.3 1722.53  5031.2 1721.99  5087.1 1721.67  5119.7 1721.32
  5253.7 1722.33  5273.4 1722.46  5373.5 1724.37  5449.5  1724.5  5490.3 1723.71
  5525.7 1722.25  5541.4 1723.17  5551.6 1724.67  5571.1 1725.28  5576.5 1725.39
#Mann= 8 ,-1 , 0
  4512.4     .05       0  4972.1    .075       0  4994.3     .07       0
    5007    .075       0  5087.1     .05       0  5253.7    .075       0
  5273.4      .1       0  5571.1    .075       0
Bank Sta=4994.3,5007
XS Rating Curve= 0 ,0
Exp/Cntr=0.3,0.1

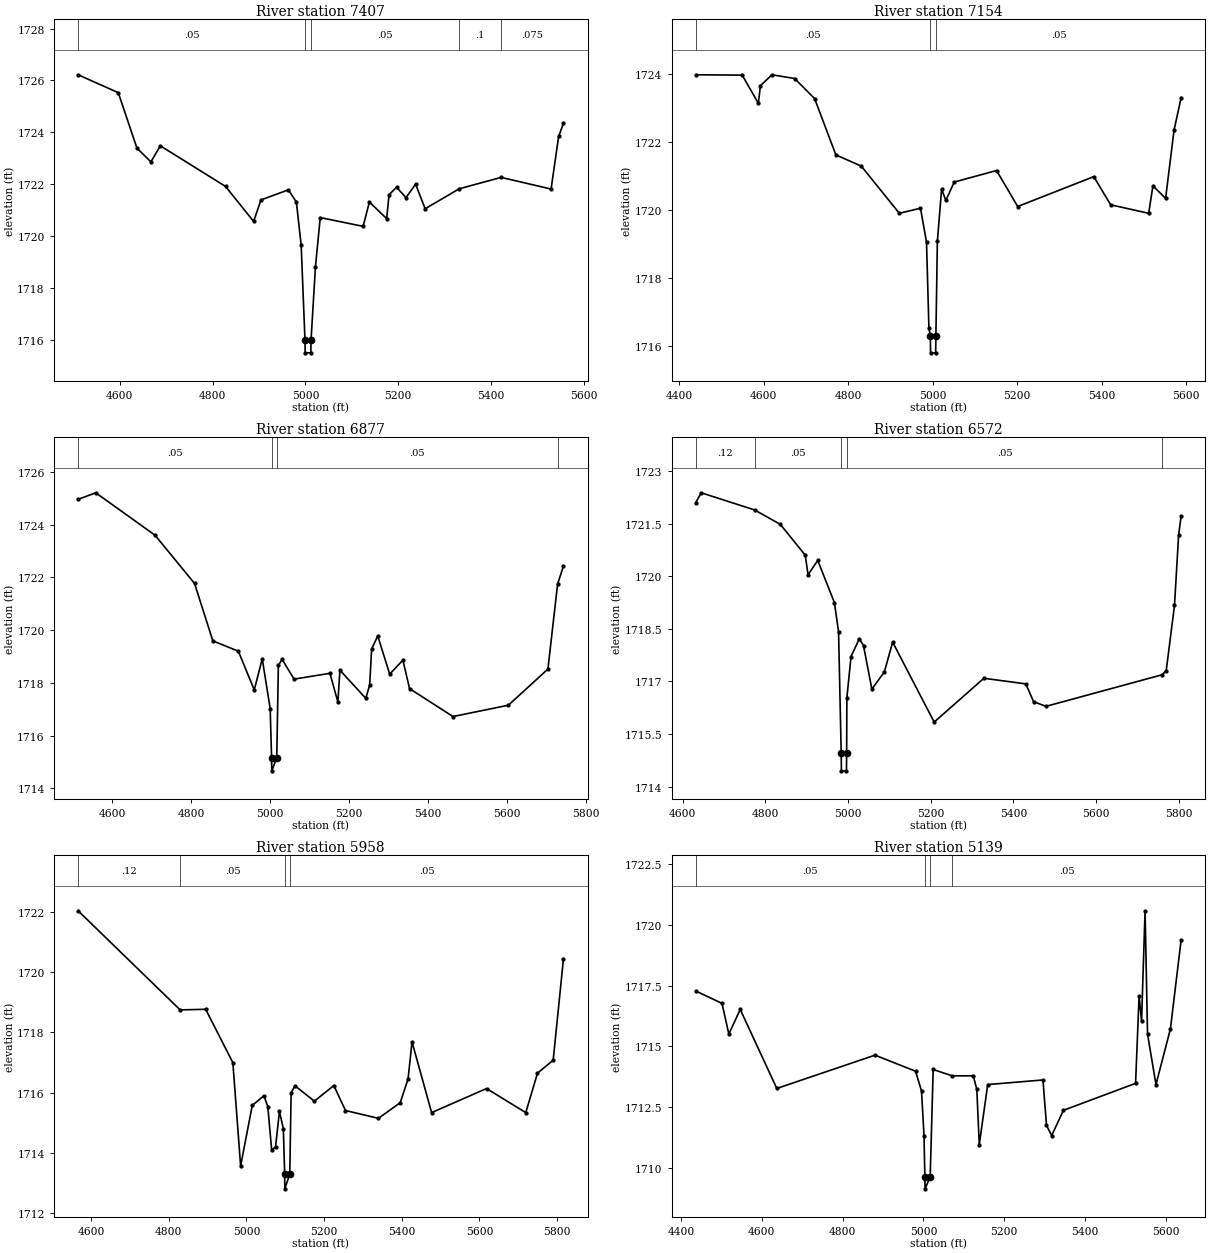
Type RM Length L Ch R = 1 ,7407    ,253,253,253
BEGIN DESCRIPTION:
Mapping XS 41c7092e
END DESCRIPTION:
XS GIS Cut Line= 3
      1608885.37      6845012.03      1608927.04      6845404.41
      1609076.34      6846038.07
#Sta/Elev= 30
  4510.3 1726.22  4596.8 1725.53    4637 1723.39  4667.1 1722.86  4687.3 1723.48
    4828 1721.91  4888.4 1720.56  4904.2 1721.39  4963.2 1721.78  4980.5 1721.31
  4990.8 1719.65    4999 1715.99  4999.5 1715.49  5011.6 1715.49  5012.1 1715.99
  5021.6 1718.82  5031.9 1720.71  5124.3 1720.37  5137.8 1721.31    5175 1720.67
  5180.1 1721.59  5196.2 1721.88  5216.8 1721.48  5237.3    1722  5257.9 1721.05
  5331.3 1721.82  5421.6 1722.26  5529.2 1721.81  5545.5 1723.84  5555.9 1724.35
#Mann= 5 ,-1 , 0
  4510.3     .05       0    4999     .03       0  5012.1     .05       0
  5331.3      .1       0  5421.6    .075       0
Bank Sta=4999,5012.1
XS Rating Curve= 0 ,0
Exp/Cntr=0.3,0.1

Type RM Length L Ch R = 1 ,7154    ,277,277,277
BEGIN DESCRIPTION:
Mapping XS b6c6c056
END DESCRIPTION:
XS GIS Cut Line= 4
      1608758.63      6844979.08      1608715.23      6845328.02
      1608699.61      6845906.15      1608699.61      6846124.78
#Sta/Elev= 30
  4439.3 1723.98  4549.1 1723.97  4587.3 1723.14  4592.3 1723.66  4619.6 1723.98
  4673.2 1723.87  4720.4 1723.28  4770.8 1721.62  4830.9 1721.29    4921  1719.9
    4971 1720.05  4985.3 1719.05    4991 1716.51  4994.4 1716.29  4994.9 1715.79
    5007 1715.79  5007.5 1716.29    5011 1719.08    5021 1720.61    5031 1720.28
    5051 1720.82    5151 1721.16  5201.1  1720.1  5381.1 1720.98  5421.1 1720.15
  5511.1  1719.9  5521.1 1720.71  5551.1 1720.34  5571.1 1722.35  5587.9 1723.31
#Mann= 3 ,-1 , 0
  4439.3     .05       0  4994.4     .03       0  5007.5     .05       0
Bank Sta=4994.4,5007.5
XS Rating Curve= 0 ,0
Exp/Cntr=0.3,0.1

Type RM Length L Ch R = 1 ,6877    ,305,305,305
BEGIN DESCRIPTION:
Mapping XS ca13cd3f
END DESCRIPTION:
XS GIS Cut Line= 4
      1608480.86      6844963.41      1608484.33      6845270.73
      1608420.09      6845781.15      1608414.88      6846187.43
#Sta/Elev= 30
  4514.5 1724.96  4559.1 1725.21  4709.1  1723.6  4809.1 1721.77  4855.4 1719.59
  4919.9  1719.2  4960.2 1717.73  4980.4 1718.91  5000.5 1717.02    5004 1715.16
  5004.5 1714.66  5017.1 1715.16  5021.2 1718.66  5030.7 1718.89    5061 1718.14
  5151.7 1718.36  5171.8 1717.27  5176.9 1718.48  5242.4 1717.41  5252.2 1717.92
  5257.2 1719.28  5272.6 1719.78  5302.9 1718.33  5336.3 1718.86  5353.1 1717.78
  5463.1 1716.72  5603.2 1717.15  5703.2 1718.52  5727.8 1721.75  5742.6 1722.43
#Mann= 4 ,-1 , 0
  4514.5     .05       0    5004     .03       0  5017.1     .05       0
  5727.8    .075       0
Bank Sta=5004,5017.1
XS Rating Curve= 0 ,0
Exp/Cntr=0.3,0.1

Type RM Length L Ch R = 1 ,6572    ,614,614,614
BEGIN DESCRIPTION:
Mapping XS 1ad597df
END DESCRIPTION:
XS GIS Cut Line= 3
       1608137.1      6845045.01      1608199.61      6845560.66
      1608248.13      6846214.04
#Sta/Elev= 30
  4631.5  1722.1  4644.6 1722.38  4773.9 1721.89    4836 1721.48  4896.4  1720.6
  4903.2 1720.04  4926.6 1720.45  4966.9 1719.25    4977 1718.42  4983.4 1714.95
  4983.9 1714.45  4996.1 1714.45  4996.6 1714.95  4997.1 1716.53  5007.2 1717.71
  5027.4 1718.22  5037.4 1718.02  5057.6 1716.78  5087.8 1717.27  5107.9 1718.12
  5208.4 1715.84  5328.7 1717.09  5430.1 1716.93  5449.1 1716.42  5479.2 1716.29
    5760 1717.19    5770 1717.31    5790 1719.17    5800 1721.18  5806.1 1721.72
#Mann= 5 ,-1 , 0
  4631.5     .12       0  4773.9     .05       0  4983.4     .03       0
  4996.6     .05       0    5760    .075       0
Bank Sta=4983.4,4996.6
XS Rating Curve= 0 ,0
Exp/Cntr=0.3,0.1

Type RM Length L Ch R = 1 ,5958    ,819,819,819
BEGIN DESCRIPTION:
Mapping XS 97116772
END DESCRIPTION:
XS GIS Cut Line= 4
      1607729.12      6845060.68      1607753.43      6845328.02
      1607753.43      6845784.62      1607826.17      6846304.21
#Sta/Elev= 30
  4566.7 1722.04  4829.4 1718.75  4895.1 1718.77  4965.1    1717  4985.1 1713.57
  5015.1 1715.58  5045.1  1715.9  5055.1 1715.54  5065.1 1714.09  5075.1 1714.21
  5085.1 1715.38  5095.1 1714.81  5098.5 1713.31    5099 1712.81  5111.7 1713.31
  5115.1    1716  5125.1 1716.23  5175.1 1715.72  5225.1 1716.24  5255.1 1715.41
  5339.9 1715.15  5396.1 1715.67  5416.3 1716.46  5426.4 1717.69  5476.9 1715.34
  5618.3 1716.14  5719.3 1715.34  5749.5 1716.65  5789.9 1717.08  5816.4 1720.45
#Mann= 4 ,-1 , 0
  4566.7     .12       0  4829.4     .05       0  5098.5     .03       0
  5111.7     .05       0
Bank Sta=5098.5,5111.7
XS Rating Curve= 0 ,0
Exp/Cntr=0.3,0.1

Type RM Length L Ch R = 1 ,5139    ,1054,1054,1054
BEGIN DESCRIPTION:
Mapping XS c90452c0
END DESCRIPTION:
XS GIS Cut Line= 4
      1606982.57      6845293.26      1607116.27      6845571.08
      1607234.33      6845642.26      1607668.36      6846260.32
#Sta/Elev= 30
  4436.6 1717.28  4501.4 1716.77  4518.4 1715.51  4546.6 1716.52  4637.1 1713.27
  4880.2 1714.64  4980.5 1713.98  4995.3 1713.17  5001.5 1711.33  5003.6 1709.64
  5004.1 1709.14  5016.8 1709.64  5024.2 1714.05  5071.1 1713.79  5123.5 1713.79
  5132.2 1713.23  5138.3 1710.96  5159.2 1713.43    5296 1713.62  5304.7 1711.75
  5317.5 1711.33  5346.5 1712.37  5525.2 1713.48  5533.9 1717.08    5540 1716.04
  5548.7 1720.58  5554.8 1715.51  5575.7 1713.43  5611.4 1715.72    5638 1719.38
#Mann= 4 ,-1 , 0
  4436.6     .05       0  5003.6     .05       0  5016.8     .05       0
  5071.1     .05       0
Bank Sta=5003.6,5016.8
XS Rating Curve= 0 ,0
Exp/Cntr=0.3,0.1

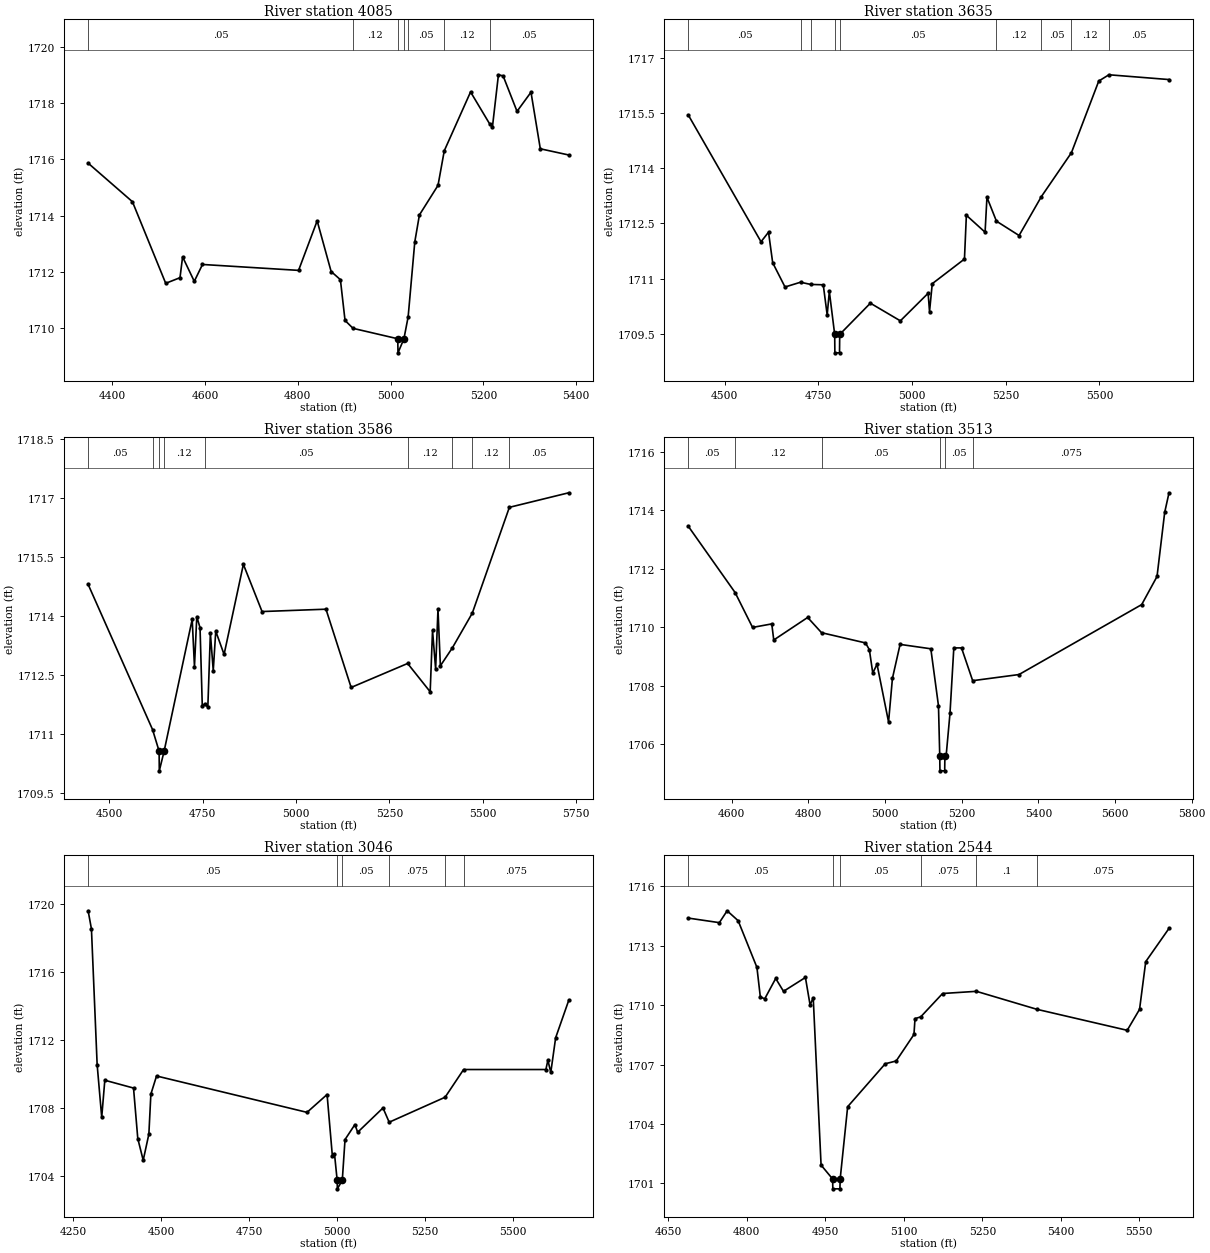
Type RM Length L Ch R = 1 ,4085    ,450,450,450
BEGIN DESCRIPTION:
Mapping XS d63f245f
END DESCRIPTION:
XS GIS Cut Line= 3
      1606774.27      6845374.94      1606868.01      6845782.89
      1606911.41      6846399.18
#Sta/Elev= 30
  4347.8 1715.87  4443.3  1714.5  4515.1  1711.6  4545.9  1711.8  4551.5 1712.54
  4576.7 1711.67  4594.4 1712.27  4801.6 1712.06  4841.7 1713.82  4871.8 1712.02
  4891.8 1711.73  4901.8 1710.28  4919.1    1710  5015.5 1709.63    5016 1709.13
  5028.8 1709.63  5037.9 1710.41  5052.2 1713.07  5062.2 1714.03  5102.3 1715.08
  5115.8 1716.31  5172.5  1718.4  5214.2 1717.25  5219.7 1717.16  5232.6 1719.01
  5242.7 1718.97  5272.7 1717.71  5302.8 1718.39  5322.9 1716.38  5384.2 1716.16
#Mann= 7 ,-1 , 0
  4347.8     .05       0  4919.1     .12       0  5015.5     .07       0
  5028.8     .12       0  5037.9     .05       0  5115.8     .12       0
  5214.2     .05       0
Bank Sta=5015.5,5028.8
XS Rating Curve= 0 ,0
Exp/Cntr=0.3,0.1

Type RM Length L Ch R = 1 ,3635    ,49,49,49
BEGIN DESCRIPTION:
Mapping XS 1c0724a9
END DESCRIPTION:
XS GIS Cut Line= 6
      1606648.83       6845331.5      1606585.02      6845559.36
      1606473.04      6845754.67      1606474.35      6845929.15
       1606755.6      6846067.17      1606815.32      6846383.97
#Sta/Elev= 30
  4403.5 1715.44  4597.2    1712  4617.2 1712.26  4628.3 1711.43  4661.2 1710.77
  4702.6  1710.9  4729.6 1710.84  4763.2 1710.83  4773.7 1710.01  4779.4 1710.65
  4793.7 1709.48  4794.2 1708.98  4806.6 1708.98  4807.1 1709.48  4888.9 1710.33
  4968.9 1709.85    5043  1710.6  5046.7  1710.1    5054 1710.86  5139.9 1711.53
    5145 1712.72  5194.9 1712.26  5199.9 1713.21  5225.2 1712.56  5285.6 1712.17
  5345.2 1713.23  5425.2 1714.42  5498.2 1716.37  5525.3 1716.54  5685.6 1716.41
#Mann= 9 ,-1 , 0
  4403.5     .05       0  4702.6     .12       0  4729.6     .05       0
  4793.7     .05       0  4807.1     .05       0  5225.2     .12       0
  5345.2     .05       0  5425.2     .12       0  5525.3     .05       0
Bank Sta=4793.7,4807.1
XS Rating Curve= 0 ,0
Exp/Cntr=0.3,0.1

Type RM Length L Ch R = 1 ,3586    ,73,73,73
BEGIN DESCRIPTION:
Mapping XS 001171b3
END DESCRIPTION:
XS GIS Cut Line= 6
      1606586.32      6845378.42       1606570.7       6845522.9
      1606423.57      6845742.95      1606441.79      6845982.54
      1606743.88      6846078.89       1606788.1      6846383.26
#Sta/Elev= 30
    4443  1714.8  4615.5 1711.11  4633.1 1710.56  4633.6 1710.06  4646.5 1710.56
  4721.7 1713.91  4727.8 1712.71    4734 1713.98  4742.7  1713.7  4748.7 1711.72
  4755.2 1711.76  4763.6 1711.68  4770.4 1713.56  4778.1 1712.61  4784.8 1713.61
  4807.1 1713.02  4858.8 1715.31  4908.8 1714.11    5080 1714.17  5147.4 1712.18
  5298.7 1712.79  5359.1 1712.07  5365.4 1713.63  5373.7 1712.65    5380 1714.17
  5386.4 1712.73  5418.7 1713.19  5471.9 1714.07  5571.2 1716.76  5730.2 1717.13
#Mann= 9 ,-1 , 0
    4443     .05       0  4615.5     .12       0  4633.1     .05       0
  4646.5     .12       0  4755.2     .05       0  5298.7     .12       0
  5418.7     .05       0  5471.9     .12       0  5571.2     .05       0
Bank Sta=4633.1,4646.5
XS Rating Curve= 0 ,0
Exp/Cntr=0.3,0.1

Type RM Length L Ch R = 1 ,3513    ,467,467,467
BEGIN DESCRIPTION:
Mapping XS 74fd7b33
END DESCRIPTION:
XS GIS Cut Line= 5
      1606436.58       6845386.2      1606366.27      6845651.81
      1606346.74      6845821.08      1606359.76      6845979.93
      1606380.02      6846629.28
#Sta/Elev= 30
  4486.7 1713.44  4608.6 1711.18  4654.1 1709.99  4704.2 1710.11  4709.4 1709.56
  4797.9 1710.33  4834.1 1709.81  4948.8 1709.46  4958.9 1709.23  4967.8 1708.43
  4978.9 1708.73    5009 1706.76  5019.1 1708.25  5039.1 1709.41  5119.3 1709.26
  5139.3 1707.31  5142.6 1705.59  5143.1 1705.09  5155.5 1705.09    5156 1705.59
  5159.3 1705.61  5169.3 1707.05  5179.3 1709.29  5199.4 1709.29  5228.5 1708.17
  5349.4 1708.38  5669.6 1710.77  5709.6 1711.73  5729.6 1713.92  5740.9 1714.59
#Mann= 6 ,-1 , 0
  4486.7     .05       0  4608.6     .12       0  4834.1     .05       0
  5142.6     .05       0    5156     .05       0  5228.5    .075       0
Bank Sta=5142.6,5156
XS Rating Curve= 0 ,0
Exp/Cntr=0.3,0.1

Type RM Length L Ch R = 1 ,3046    ,502,502,502
BEGIN DESCRIPTION:
Mapping XS d51848bd
END DESCRIPTION:
XS GIS Cut Line= 4
      1605585.78      6845484.15      1605736.69      6845760.27
      1606113.67      6846319.78      1606288.77      6846653.17
#Sta/Elev= 30
  4292.6 1719.61    4302 1718.54  4318.2 1710.56  4331.2 1707.46    4340 1709.64
  4421.6 1709.18  4433.7 1706.21  4449.1 1704.93  4465.2 1706.47  4470.9 1708.82
    4487 1709.89  4914.7 1707.75  4971.7  1708.8  4986.7 1705.19  4992.7 1705.32
  5000.4 1703.75  5000.9 1703.25  5014.9 1703.75  5022.7 1706.15  5050.7 1707.03
  5058.7 1706.58  5130.6 1708.01  5148.2 1707.17  5307.1 1708.64  5359.7 1710.27
  5593.6 1710.27  5599.2 1710.82  5607.5  1710.1  5621.3 1712.14  5658.5 1714.34
#Mann= 6 ,-1 , 0
  4292.6     .05       0  5000.4     .03       0  5014.9     .05       0
  5148.2    .075       0  5307.1      .1       0  5359.7    .075       0
Bank Sta=5000.4,5014.9
XS Rating Curve= 0 ,0
Exp/Cntr=0.3,0.1

Type RM Length L Ch R = 1 ,2544    ,325,325,325
BEGIN DESCRIPTION:
Mapping XS 6c7b3f0e
END DESCRIPTION:
XS GIS Cut Line= 3
       1605371.5       6846239.5      1605727.38      6846482.54
      1606175.98      6846673.24
#Sta/Elev= 30
  4688.3  1714.4  4747.4 1714.17  4762.3 1714.77  4783.3 1714.27  4819.2 1711.91
  4825.7 1710.42  4834.1 1710.32  4855.1 1711.35    4870  1710.7  4911.9  1711.4
  4920.8 1710.01  4926.8 1710.38  4941.8 1701.92  4963.8 1701.22  4964.3 1700.72
  4977.8 1700.72  4978.3 1701.22  4992.6 1704.87  5064.4 1707.04  5085.3 1707.18
  5119.3 1708.52  5121.3 1709.32  5132.2 1709.41    5174 1710.59  5238.6  1710.7
  5354.4 1709.79  5526.8 1708.73  5550.4 1709.79  5562.2  1712.2  5606.7 1713.88
#Mann= 6 ,-1 , 0
  4688.3     .05       0  4963.8     .05       0  4978.3     .05       0
  5132.2    .075       0  5238.6      .1       0  5354.4    .075       0
Bank Sta=4963.8,4978.3
XS Rating Curve= 0 ,0
Exp/Cntr=0.3,0.1