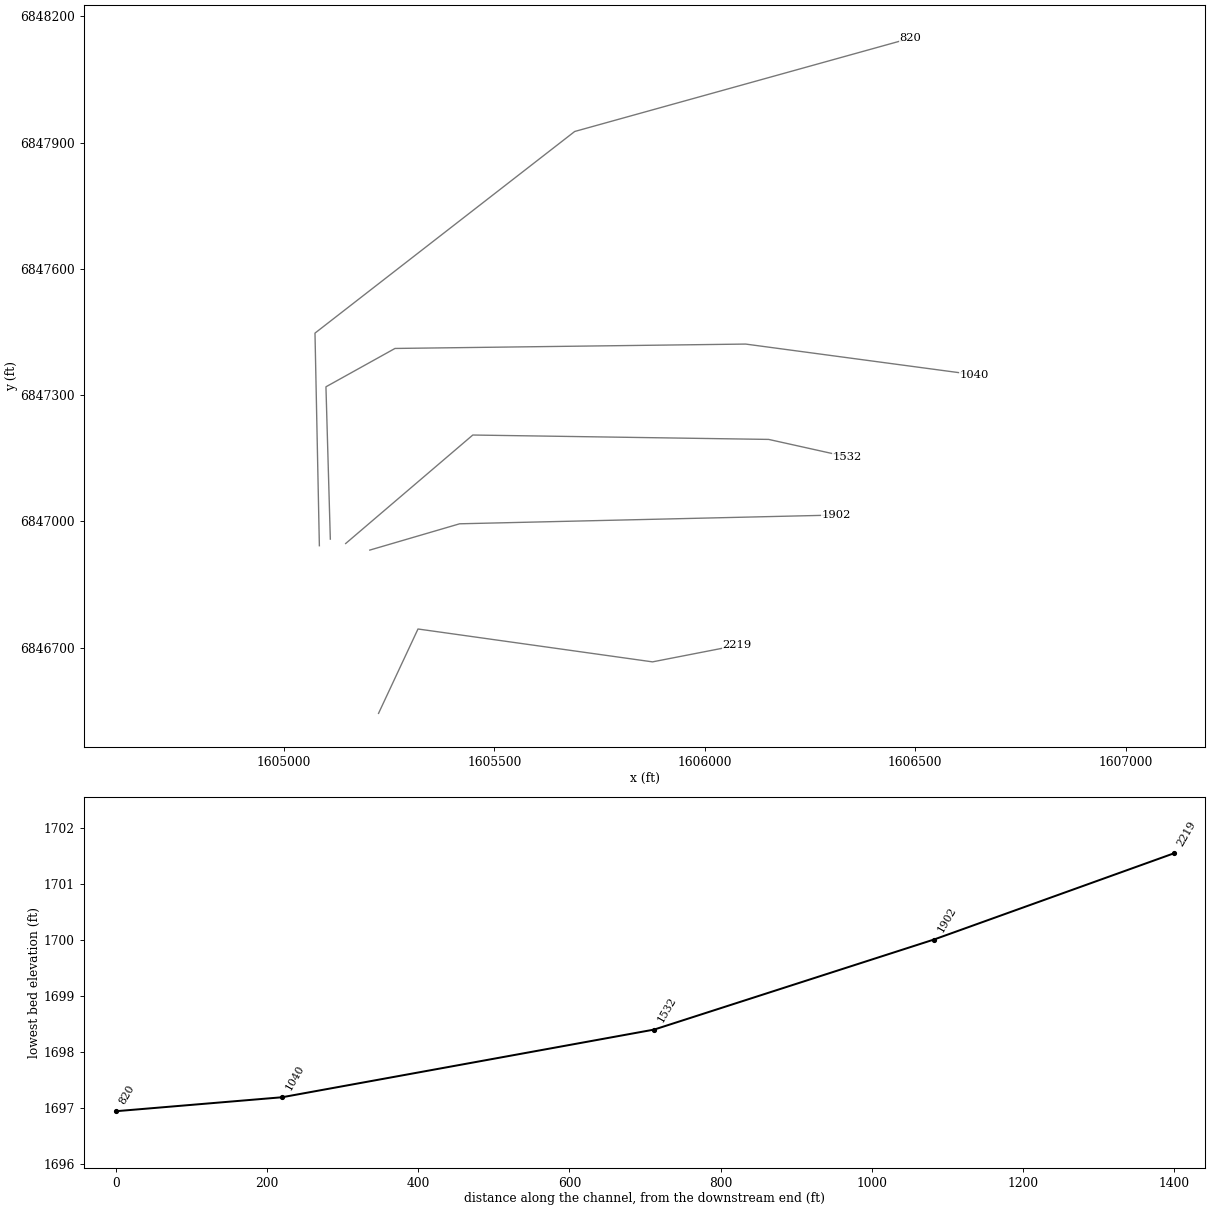
HEC-RAS study Elm 02 23.prj: Elm 02 23 Base Level Engineering

--- Elm 02 23.g01 (geometry) --- (continued)

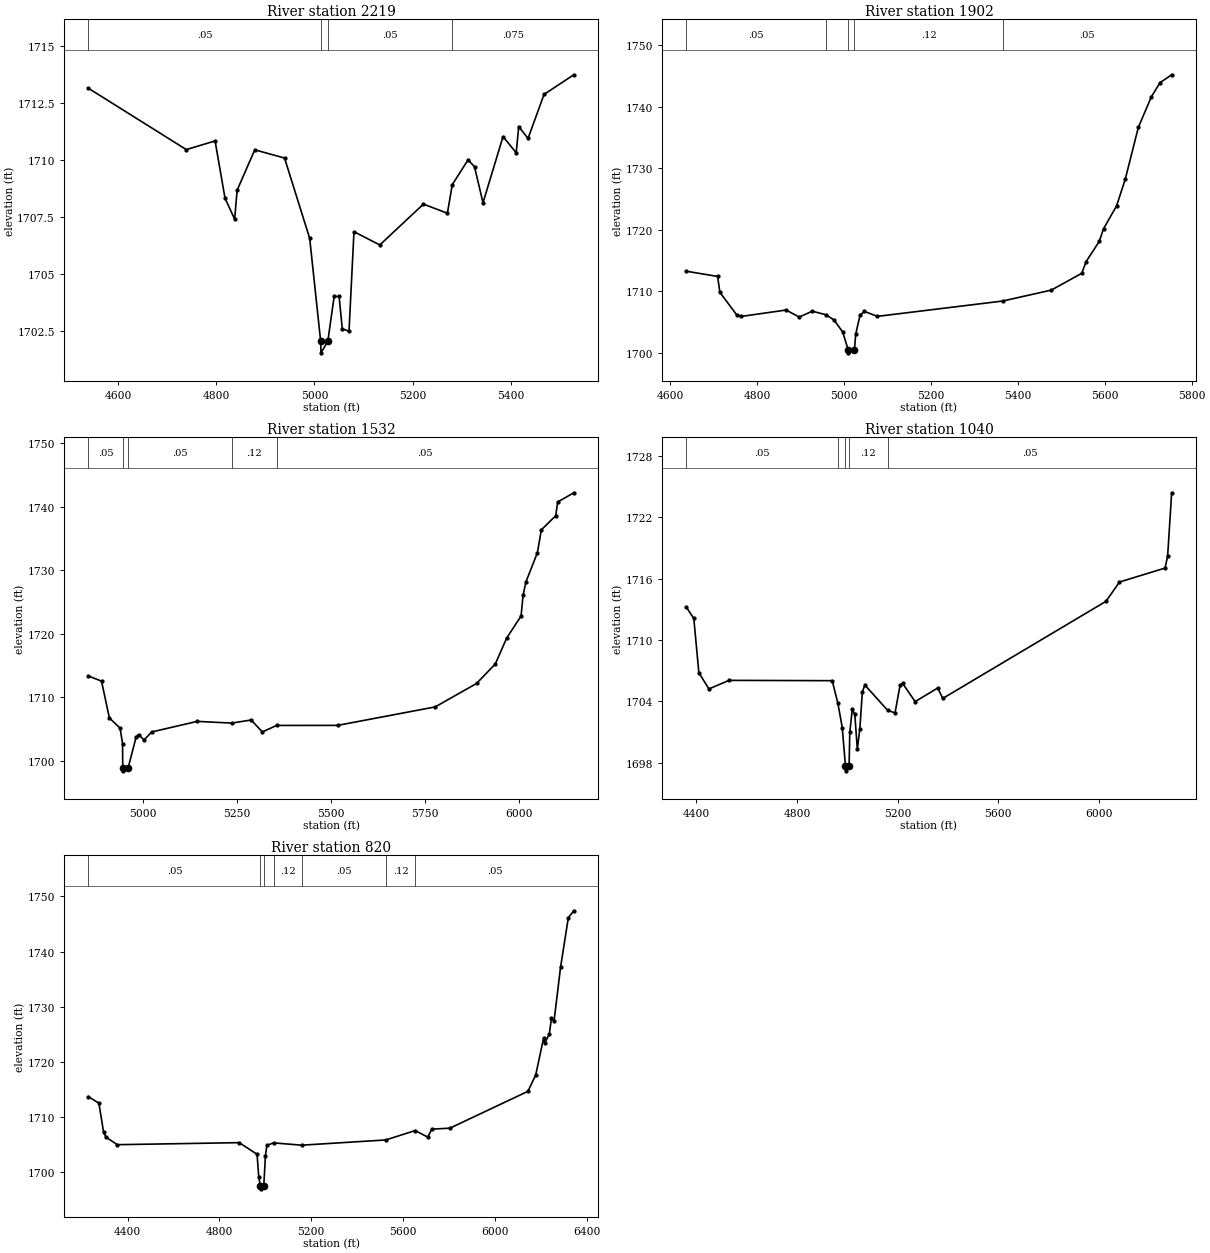
Type RM Length L Ch R = 1 ,2219    ,317,317,317
BEGIN DESCRIPTION:
Mapping XS adc44b93
END DESCRIPTION:
XS GIS Cut Line= 4
      1605224.91      6846543.71      1605318.66      6846744.23
      1605875.95      6846666.11      1606076.49      6846705.17
#Sta/Elev= 30
  4539.7 1713.15  4739.1 1710.46  4797.7 1710.84  4817.9 1708.33  4837.5 1707.41
  4842.6 1708.68  4878.5 1710.45  4939.1 1710.09  4990.3 1706.57  5012.7 1702.05
  5013.2 1701.55  5027.2 1702.05  5040.1 1704.02  5050.2 1704.02  5056.7  1702.6
  5070.4  1702.5  5080.5 1706.86  5133.1 1706.28  5221.9 1708.07  5270.7 1707.67
  5280.6 1708.92  5312.7 1710.01  5325.9 1709.71  5343.2 1708.13    5384 1711.03
  5410.8 1710.32  5415.9 1711.47  5434.9 1710.95  5467.5 1712.88  5528.1 1713.74
#Mann= 4 ,-1 , 0
  4539.7     .05       0  5012.7     .03       0  5027.2     .05       0
  5280.6    .075       0
Bank Sta=5012.7,5027.2
XS Rating Curve= 0 ,0
Exp/Cntr=0.3,0.1

Type RM Length L Ch R = 1 ,1902    ,370,370,370
BEGIN DESCRIPTION:
Mapping XS 74387572
END DESCRIPTION:
XS GIS Cut Line= 3
       1605204.1      6846931.74      1605417.62      6846994.23
       1606311.7      6847015.03
#Sta/Elev= 30
  4637.2 1713.28  4709.4 1712.43  4714.6 1709.85  4753.2 1706.19  4763.2 1705.92
  4867.1 1706.97  4897.1 1705.82  4927.1 1706.78  4958.6  1706.2  4977.1 1705.36
  4997.1 1703.41  5009.8 1700.51  5010.3 1700.01  5024.3 1700.51  5027.1 1703.03
  5037.1 1706.14  5047.1 1706.74  5077.1 1705.94  5365.1 1708.43  5477.2 1710.21
  5547.2 1712.94  5557.2 1714.84  5587.3 1718.11  5597.3 1720.18  5627.3  1723.9
  5647.3 1728.25  5677.3 1736.65  5707.3 1741.63  5727.3 1743.93    5754 1745.21
#Mann= 5 ,-1 , 0
  4637.2     .05       0  4958.6     .12       0  5009.8     .07       0
  5024.3     .12       0  5365.1     .05       0
Bank Sta=5009.8,5024.3
XS Rating Curve= 0 ,0
Exp/Cntr=0.3,0.1

Type RM Length L Ch R = 1 ,1532    ,492,492,492
BEGIN DESCRIPTION:
Mapping XS dc94390c
END DESCRIPTION:
XS GIS Cut Line= 4
      1605146.77      6846947.34      1605448.87      6847205.17
      1606151.99      6847194.75      1606339.45       6847153.1
#Sta/Elev= 30
  4854.6 1713.34  4889.6 1712.53  4910.5 1706.73    4939 1705.13  4945.6  1702.7
  4946.1  1698.9  4946.6  1698.4  4960.6  1698.9  4981.9 1703.77  4988.4 1704.11
  5002.7 1703.27  5023.6 1704.53  5144.3 1706.19  5236.5 1705.92  5287.9 1706.41
  5317.9 1704.53  5355.7 1705.55  5517.9 1705.56    5778 1708.47    5888 1712.16
    5938 1715.23  5968.3 1719.32  6006.6 1722.79  6011.8 1726.02  6019.5 1728.15
  6050.2 1732.79  6060.5 1736.36  6098.8 1738.58    6104 1740.75    6147  1742.2
#Mann= 5 ,-1 , 0
  4854.6     .05       0  4946.1     .05       0  4960.6     .05       0
  5236.5     .12       0  5355.7     .05       0
Bank Sta=4946.1,4960.6
XS Rating Curve= 0 ,0
Exp/Cntr=0.3,0.1

Type RM Length L Ch R = 1 ,1040    ,220,220,220
BEGIN DESCRIPTION:
Mapping XS ca00df03
END DESCRIPTION:
XS GIS Cut Line= 5
      1605110.33       6846957.8      1605099.91      6847319.75
      1605263.97       6847410.9      1606097.31      6847421.32
      1606640.77      6847348.51
#Sta/Elev= 30
  4359.3 1713.24  4389.5 1712.11  4409.5 1706.81  4449.5 1705.21  4529.6 1706.05
  4940.1 1706.02  4962.7 1703.81  4980.1 1701.43  4992.8 1697.69  4993.3 1697.19
  5007.4 1697.69  5010.1 1700.97  5020.1 1703.22  5030.1 1702.72  5040.1  1699.3
  5050.1  1701.3  5060.1 1704.92  5070.1 1705.59  5160.6 1703.12  5190.1 1702.86
  5210.1 1705.56  5220.1 1705.76  5270.1 1703.97  5360.1  1705.3  5380.1 1704.28
  6029.4 1713.79  6083.2 1715.68  6264.8 1717.05  6274.9 1718.26  6290.8 1724.42
#Mann= 5 ,-1 , 0
  4359.3     .05       0  4962.7     .12       0  4992.8     .07       0
  5007.4     .12       0  5160.6     .05       0
Bank Sta=4992.8,5007.4
XS Rating Curve= 0 ,0
Exp/Cntr=0.3,0.1

Type RM Length L Ch R = 1 ,820     ,0,0,0
BEGIN DESCRIPTION:
Elm 02 23 9939.3
END DESCRIPTION:
XS GIS Cut Line= 4
      1605084.29      6846942.13      1605073.87      6847447.36
      1605691.06      6847926.52      1606487.89      6848147.87
#Sta/Elev= 30
  4229.5 1713.67  4275.4 1712.48  4295.4  1707.3  4305.4 1706.35  4355.4 1704.95
  4886.3 1705.32  4964.1 1703.21  4971.4 1699.06  4978.6 1697.44  4979.1 1696.94
  4993.2 1697.44  5000.4 1702.91  5006.7 1704.81  5035.6 1705.28  5158.2 1704.86
  5524.5 1705.81  5652.2 1707.51  5707.1 1706.33  5724.9 1707.77  5803.8 1707.95
  6143.2 1714.63  6177.4  1717.6  6211.7 1724.32  6216.9  1723.4  6236.4 1725.02
  6245.9 1727.88  6257.2  1727.4  6285.4 1737.13  6319.4 1746.15  6343.2 1747.39
#Mann= 7 ,-1 , 0
  4229.5     .05       0  4978.6     .05       0  4993.2     .05       0
  5035.6     .12       0  5158.2     .05       0  5524.5     .12       0
  5652.2     .05       0
Bank Sta=4978.6,4993.2
XS Rating Curve= 0 ,0
Exp/Cntr=0.3,0.1

Chan Stop Cuts=-1
Use User Specified Reach Order=0
Composite Channel Slope=5