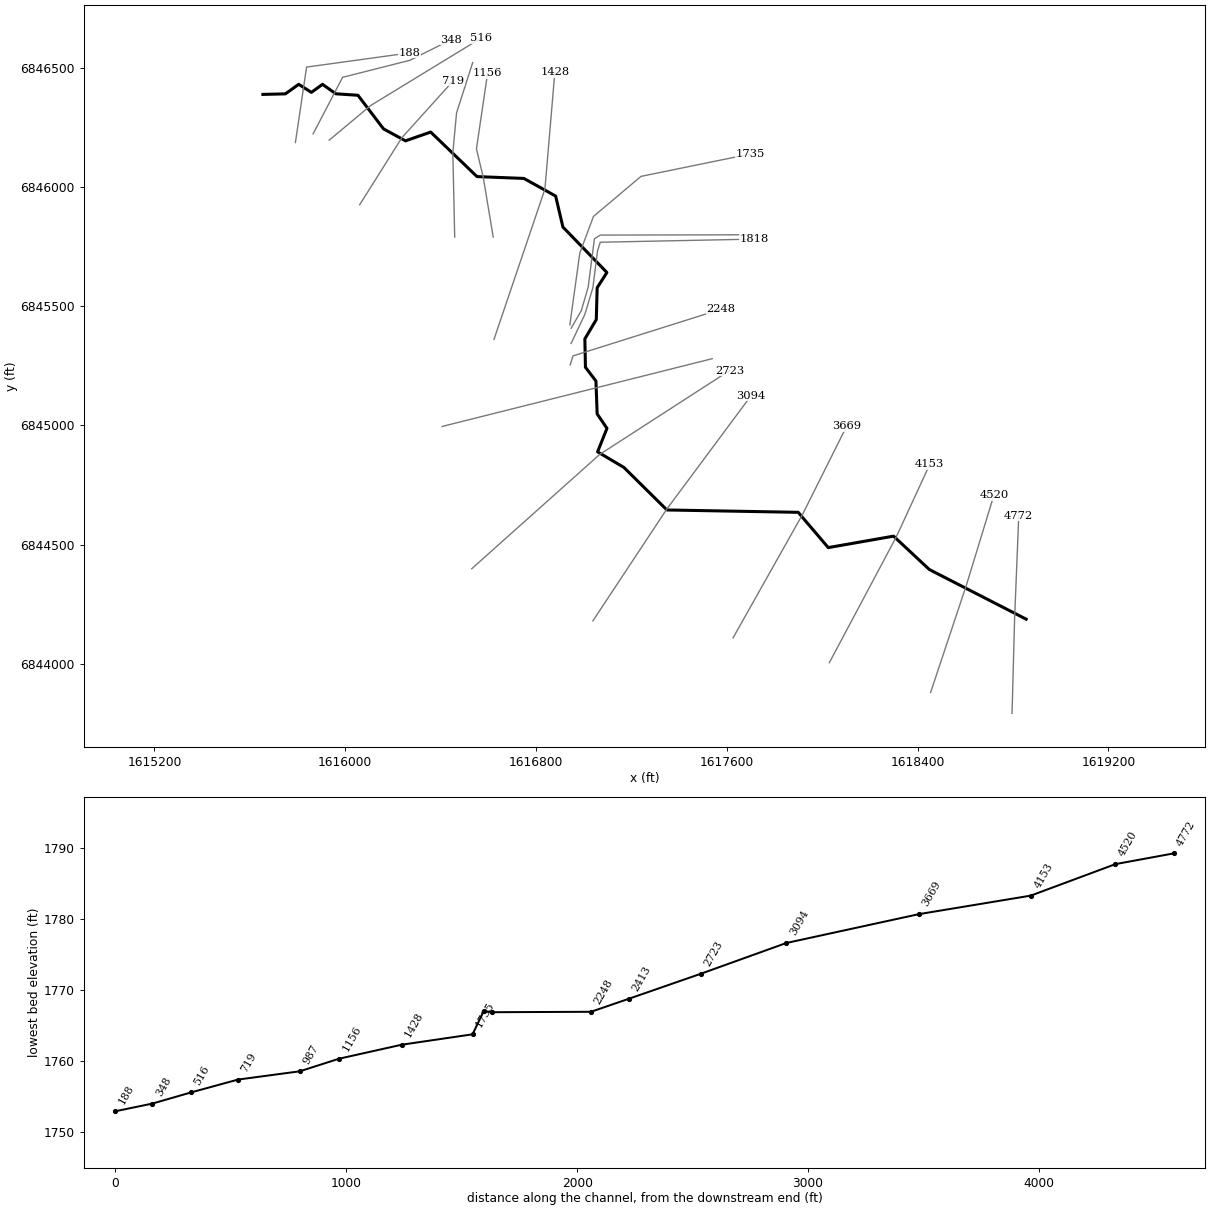
--- Elm 02 24.prj (project) ---

Proj Title=Elm 02 24 Base Level Engineering
Current Plan=p01
Default Exp/Contr=0.3,0.1
English Units
Geom File=g01
Flow File=f01
Plan File=p01
BEGIN DESCRIPTION:
Elm 02 24
END DESCRIPTION:

--- Elm 02 24.p01 (plan) ---

Plan Title=Multiple Run
Short Identifier=Multiple
Geom File=g01
Flow File=f01
Subcritical Flow
K Sum by GR= 0
Std Step Tol= 0.01
Critical Tol= 0.01
Num of Std Step Trials= 20
Max Error Tol= 0.3
Flow Tol Ratio= 0.001
Split Flow NTrial= 30
Split Flow Tol= 0.02
Split Flow Ratio= 0.02
Log Output Level= 0
Friction Slope Method= 1
Unsteady Friction Slope Method= 2
Unsteady Bridges Friction Slope Method= 1
Parabolic Critical Depth
Global Vel Dist=  1 , 1 , 1
Global Log Level= 0
CheckData=True
Encroach Param= -1, 0, 0, 0
BEGIN DESCRIPTION:
Multiple Run
END DESCRIPTION:

--- Elm 02 24.f01 (steady flow) ---

Flow Title=Multiple
Number of Profiles=7
Profile Names=10-year,25-year,50-year,1pct_min,100-year,1pct_plu,500-year
River Rch & RM= Elm 02 24,Reach-1,4772
     150     201     242     180     289     398     418
Boundary for River Rch & Prof#=Elm 02 24,Reach-1,1
Up Type=0
Dn Type=3
Dn Slope=0.001
Boundary for River Rch & Prof#=Elm 02 24,Reach-1,2
Up Type=0
Dn Type=3
Dn Slope=0.001
Boundary for River Rch & Prof#=Elm 02 24,Reach-1,3
Up Type=0
Dn Type=3
Dn Slope=0.001
Boundary for River Rch & Prof#=Elm 02 24,Reach-1,4
Up Type=0
Dn Type=3
Dn Slope=0.001
Boundary for River Rch & Prof#=Elm 02 24,Reach-1,5
Up Type=0
Dn Type=3
Dn Slope=0.001
Boundary for River Rch & Prof#=Elm 02 24,Reach-1,6
Up Type=0
Dn Type=3
Dn Slope=0.001
Boundary for River Rch & Prof#=Elm 02 24,Reach-1,7
Up Type=0
Dn Type=3
Dn Slope=0.001

--- Elm 02 24.g01 (geometry) ---

Geom Title=Existing Conditions

River Reach=Elm 02 24,Reach-1
Reach XY= 30
      1618855.00      6844188.00      1618448.94      6844396.14
      1618299.11      6844536.04      1618025.20      6844488.02
      1617899.16      6844635.95      1617348.81      6844645.81
      1617168.20      6844824.36      1617058.07      6844889.43
      1617097.41      6844987.99      1617056.39      6845048.44
      1617051.21      6845186.43      1617007.25      6845243.94
      1617004.77      6845363.07      1617052.73      6845443.94
      1617056.40      6845577.56      1617097.21      6845641.42
      1616912.86      6845831.83      1616882.28      6845961.90
      1616749.07      6846035.76      1616552.55      6846043.46
      1616358.41      6846230.18      1616252.78      6846193.35
      1616160.61      6846243.59      1616053.51      6846384.39
      1615960.89      6846390.55      1615904.90      6846430.22
      1615858.33      6846396.55      1615805.10      6846430.26
      1615749.23      6846390.33      1615655.00      6846388.00

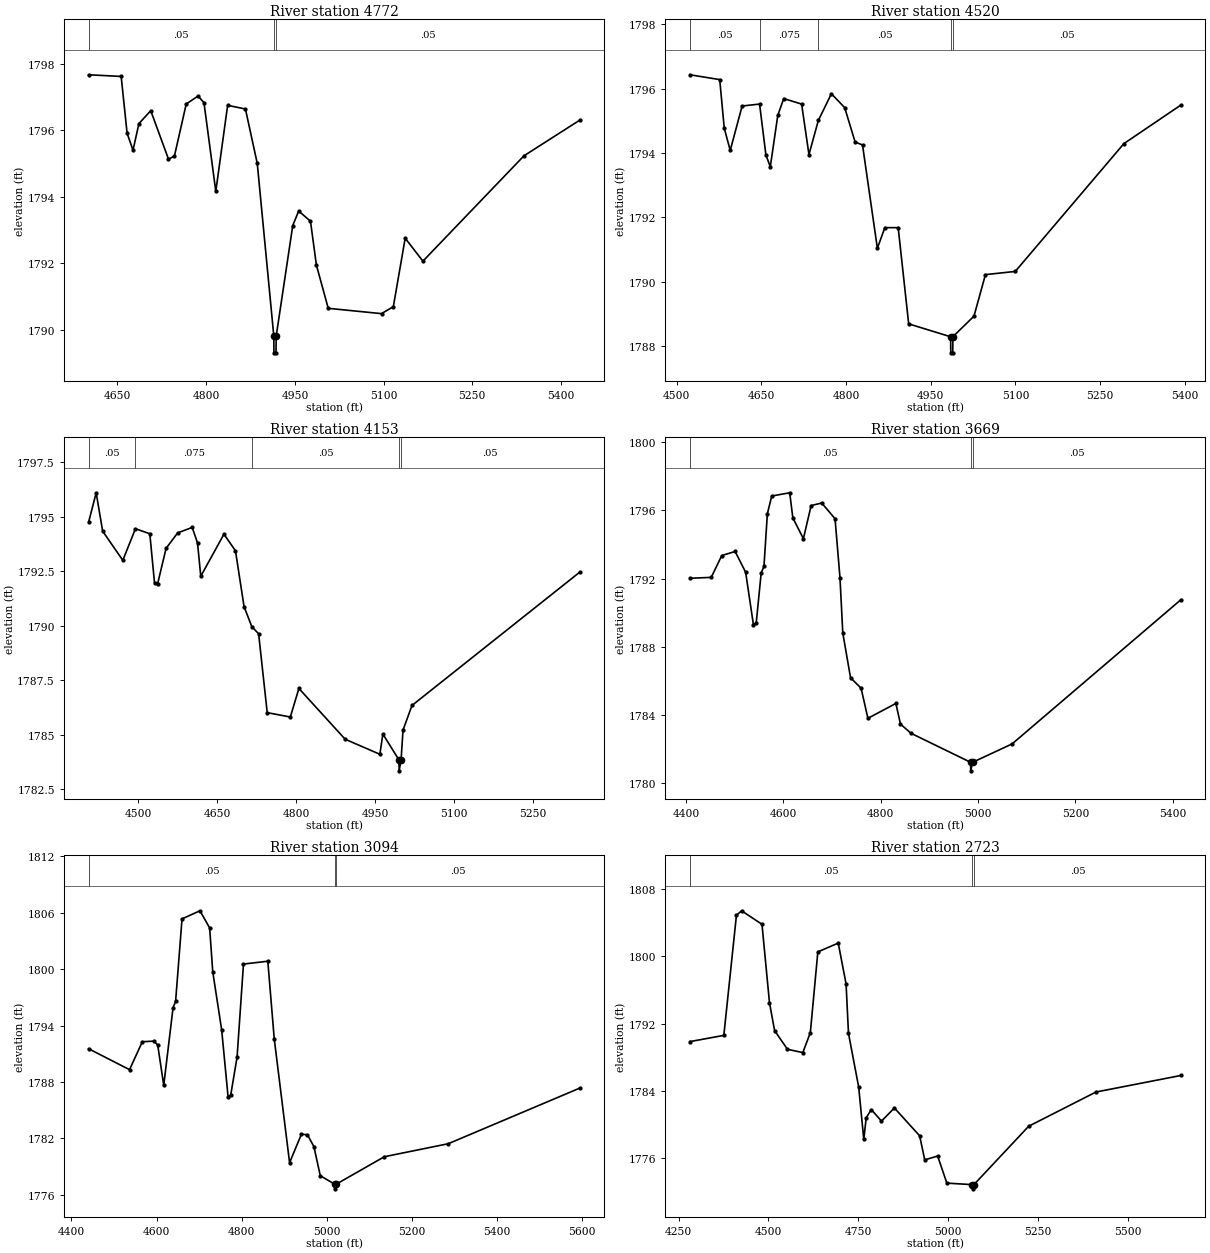
Type RM Length L Ch R = 1,4772,252,252,252
BEGIN DESCRIPTION:
Elm 02 24 4708.524
END DESCRIPTION:
XS GIS Cut Line= 3
      1618795.78      6843793.04      1618806.49      6844191.60
      1618823.99      6844622.54
#Sta/Elev= 30
  4601.3 1797.67  4656.3 1797.62  4666.3 1795.91  4676.3 1795.40  4686.3 1796.20
  4706.3 1796.59  4736.3 1795.13  4746.3 1795.22  4766.3 1796.79  4786.3 1797.03
  4796.3 1796.83  4816.3 1794.16  4836.3 1796.75  4866.4 1796.64  4886.4 1795.00
  4914.4 1789.80  4914.6 1789.30  4918.1 1789.30  4918.4 1789.80  4946.4 1793.13
  4956.4 1793.57  4976.4 1793.26  4986.4 1791.94  5006.4 1790.64  5096.5 1790.48
  5116.5 1790.69  5136.5 1792.75  5166.5 1792.06  5337.3 1795.23  5431.3 1796.30
#Mann=3,-1,0
  4601.3    0.05       0  4914.4    0.03       0  4918.4    0.05       0
Bank Sta=4914.4,4918.4
Exp/Cntr=0.3,0.1

Type RM Length L Ch R = 1,4520,367,367,367
BEGIN DESCRIPTION:
Elm 02 24 4520.31
END DESCRIPTION:
XS GIS Cut Line= 3
      1618454.20      6843880.38      1618605.25      6844333.52
      1618719.84      6844708.55
#Sta/Elev= 30
  4523.3 1796.43  4576.0 1796.28  4584.0 1794.77  4594.6 1794.08  4615.7 1795.46
  4646.6 1795.52  4657.8 1793.94  4665.6 1793.57  4678.9 1795.17  4689.4 1795.69
  4721.1 1795.52  4734.1 1793.95  4750.7 1795.01  4773.8 1795.84  4797.4 1795.41
  4815.9 1794.34  4829.0 1794.25  4855.3 1791.04  4868.6 1791.68  4892.2 1791.68
  4910.8 1788.69  4985.1 1788.29  4985.4 1787.79  4988.9 1787.79  4989.1 1788.29
  5026.5 1788.93  5046.8 1790.22  5099.7 1790.32  5292.1 1794.29  5393.1 1795.49
#Mann=5,-1,0
  4523.3    0.05       0  4646.6   0.075       0  4750.7    0.05       0
  4985.1    0.05       0  4989.1    0.05       0
Bank Sta=4985.1,4989.1
Exp/Cntr=0.3,0.1

Type RM Length L Ch R = 1,4153,484,484,484
BEGIN DESCRIPTION:
Elm 02 24 4153.31
END DESCRIPTION:
XS GIS Cut Line= 3
      1618029.72      6844005.39      1618310.98      6844534.04
      1618450.81      6844837.02
#Sta/Elev= 30
  4405.9 1794.76  4420.2 1796.10  4432.5 1794.34  4470.8 1793.00  4494.8 1794.45
  4522.1 1794.22  4531.0 1791.97  4536.7 1791.90  4553.0 1793.55  4575.0 1794.26
  4602.6 1794.51  4612.7 1793.80  4618.9 1792.27  4662.9 1794.20  4684.8 1793.44
  4701.1 1790.88  4715.8 1789.96  4728.8 1789.63  4745.1 1786.01  4789.0 1785.81
  4805.3 1787.12  4893.2 1784.79  4959.1 1784.10  4964.8 1785.03  4995.4 1783.84
  4995.7 1783.34  4999.4 1783.84  5003.1 1785.21  5020.1 1786.34  5338.4 1792.45
#Mann=5,-1,0
  4405.9    0.05       0  4494.8   0.075       0  4715.8    0.05       0
  4995.4    0.05       0  4999.4    0.05       0
Bank Sta=4995.4,4999.4
Exp/Cntr=0.3,0.1

Type RM Length L Ch R = 1,3669,575,575,575
BEGIN DESCRIPTION:
Elm 02 24 3668.92
END DESCRIPTION:
XS GIS Cut Line= 3
      1617626.07      6844109.55      1617917.75      6844627.79
      1618102.63      6844997.57
#Sta/Elev= 30
  4408.4 1792.02  4452.0 1792.07  4473.7 1793.35  4501.1 1793.59  4522.7 1792.37
  4538.7 1789.29  4544.4 1789.39  4554.6 1792.33  4560.3 1792.71  4567.3 1795.80
  4576.3 1796.84  4613.2 1797.03  4619.6 1795.56  4641.3 1794.34  4657.2 1796.28
  4678.9 1796.43  4706.3 1795.51  4716.4 1792.06  4722.2 1788.81  4738.1 1786.19
  4759.8 1785.57  4773.8 1783.81  4831.2 1784.68  4840.7 1783.47  4862.4 1782.93
  4984.7 1781.23  4984.9 1780.73  4988.7 1781.23  5070.0 1782.31  5416.5 1790.76
#Mann=3,-1,0
  4408.4    0.05       0  4984.7    0.05       0  4988.7    0.05       0
Bank Sta=4984.7,4988.7
Exp/Cntr=0.3,0.1

Type RM Length L Ch R = 1,3094,371,371,371
BEGIN DESCRIPTION:
Elm 02 24 3094.3
END DESCRIPTION:
XS GIS Cut Line= 3
      1617038.42      6844180.76      1617348.30      6844649.49
      1617701.36      6845124.56
#Sta/Elev= 30
  4440.4 1791.53  4536.5 1789.31  4566.6 1792.28  4593.6 1792.34  4602.7 1791.94
  4616.9 1787.65  4638.8 1795.89  4644.8 1796.58  4659.9 1805.33  4702.0 1806.19
  4724.8 1804.37  4732.1 1799.71  4753.1 1793.52  4768.2 1786.38  4774.2 1786.57
  4789.3 1790.65  4804.3 1800.53  4861.5 1800.83  4876.6 1792.60  4912.7 1779.43
  4940.6 1782.46  4954.8 1782.39  4969.8 1781.14  4984.9 1778.04  5018.5 1777.15
  5018.8 1776.65  5022.5 1777.15  5135.3 1780.06  5285.5 1781.44  5594.2 1787.34
#Mann=3,-1,0
  4440.4    0.05       0  5018.5    0.03       0  5022.5    0.05       0
Bank Sta=5018.5,5022.5
Exp/Cntr=0.3,0.1

Type RM Length L Ch R = 1,2723,310,310,310
BEGIN DESCRIPTION:
Elm 02 24 2723.34
END DESCRIPTION:
XS GIS Cut Line= 3
      1616530.58      6844399.48      1617067.05      6844878.66
      1617610.69      6845229.81
#Sta/Elev= 30
  4281.5 1789.85  4375.7 1790.59  4410.8 1804.90  4425.1 1805.44  4481.9 1803.83
  4502.8 1794.48  4517.0 1791.16  4552.9 1788.93  4595.6 1788.54  4616.5 1790.91
  4637.4 1800.54  4694.2 1801.59  4716.0 1796.72  4722.7 1790.83  4751.1 1784.43
  4765.3 1778.19  4772.0 1780.76  4786.2 1781.75  4814.6 1780.37  4850.5 1781.94
  4920.8 1778.62  4935.0 1775.75  4970.9 1776.21  4996.6 1772.98  5067.9 1772.80
  5068.2 1772.30  5071.9 1772.80  5224.3 1779.76  5411.7 1783.84  5648.0 1785.81
#Mann=3,-1,0
  4281.5    0.05       0  5067.9    0.03       0  5071.9    0.05       0
Bank Sta=5067.9,5071.9
Exp/Cntr=0.3,0.1

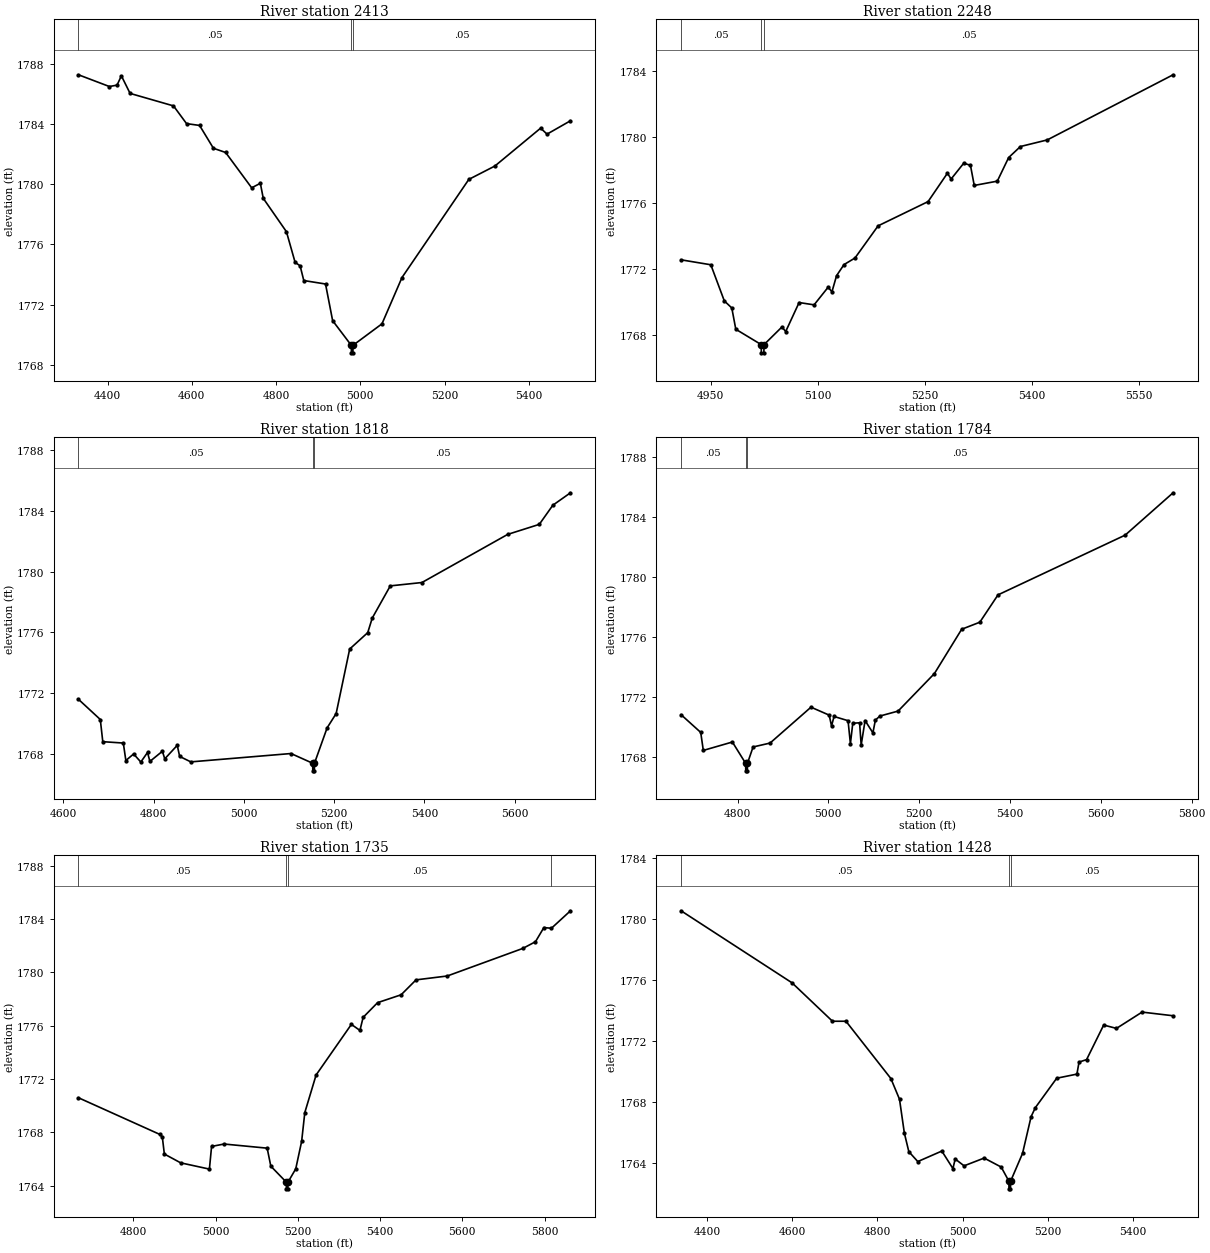
Type RM Length L Ch R = 1,2413,165,165,165
BEGIN DESCRIPTION:
Elm 02 24 2412.53
END DESCRIPTION:
XS GIS Cut Line= 3
      1616406.13      6844995.84      1617055.04      6845158.61
      1617539.00      6845280.14
#Sta/Elev= 30
  4330.8 1787.29  4404.1 1786.51  4422.4 1786.60  4432.7 1787.22  4453.4 1786.05
  4556.4 1785.22  4587.4 1784.04  4618.3 1783.92  4651.2 1782.40  4680.2 1782.12
  4742.0 1779.77  4762.6 1780.07  4769.5 1779.07  4824.5 1776.85  4845.1 1774.81
  4857.0 1774.58  4865.7 1773.60  4917.3 1773.37  4934.2 1770.93  4978.5 1769.29
  4978.8 1768.79  4982.3 1768.79  4982.5 1769.29  5051.3 1770.72  5098.8 1773.80
  5257.5 1780.33  5319.4 1781.22  5428.0 1783.74  5443.1 1783.34  5498.8 1784.23
#Mann=3,-1,0
  4330.8    0.05       0  4978.5    0.03       0  4982.5    0.05       0
Bank Sta=4978.5,4982.5
Exp/Cntr=0.3,0.1

Type RM Length L Ch R = 1,2248,430,430,430
BEGIN DESCRIPTION:
Mapping XS 5f9e29ed
END DESCRIPTION:
XS GIS Cut Line= 3
      1616943.22      6845253.96      1616954.95      6845291.74
      1617574.74      6845487.05
#Sta/Elev= 30
  4908.3 1772.58  4950.0 1772.28  4968.9 1770.09  4979.4 1769.66  4985.0 1768.37
  5020.6 1767.44  5020.8 1766.94  5024.3 1766.94  5024.6 1767.44  5049.7 1768.51
  5054.9 1768.23  5073.7 1769.99  5094.7 1769.85  5114.4 1770.92  5119.7 1770.64
  5126.2 1771.62  5136.6 1772.29  5152.0 1772.69  5184.4 1774.64  5254.4 1776.11
  5281.5 1777.83  5286.7 1777.48  5304.4 1778.44  5313.8 1778.31  5319.1 1777.09
  5351.4 1777.35  5367.3 1778.78  5383.8 1779.45  5421.4 1779.85  5597.7 1783.80
#Mann=3,-1,0
  4908.3    0.05       0  5020.6    0.03       0  5024.6    0.05       0
Bank Sta=5020.6,5024.6
Exp/Cntr=0.3,0.1

Type RM Length L Ch R = 1,1818,34,34,34
BEGIN DESCRIPTION:
Mapping XS 0809a5ab
END DESCRIPTION:
XS GIS Cut Line= 6
      1616947.13      6845343.82      1617004.42      6845464.92
      1617038.28      6845576.90      1617057.81      6845731.84
      1617069.53      6845768.30      1617714.08      6845781.32
#Sta/Elev= 30
  4633.7 1771.59  4682.1 1770.26  4687.6 1768.80  4733.1 1768.71  4738.7 1767.56
  4755.9 1767.99  4771.9 1767.46  4786.7 1768.09  4792.0 1767.50  4819.7 1768.17
  4824.9 1767.67  4852.6 1768.56  4857.9 1767.83  4882.6 1767.47  5104.6 1768.02
  5152.6 1767.38  5152.9 1766.88  5156.4 1766.88  5156.6 1767.38  5184.6 1769.71
  5204.6 1770.65  5234.6 1774.90  5274.6 1775.98  5284.6 1776.94  5324.6 1779.06
  5394.7 1779.28  5584.7 1782.45  5654.7 1783.11  5684.7 1784.37  5723.8 1785.19
#Mann=3,-1,0
  4633.7    0.05       0  5152.6    0.05       0  5156.6    0.05       0
Bank Sta=5152.6,5156.6
Exp/Cntr=0.3,0.1

Type RM Length L Ch R = 1,1784,49,49,49
BEGIN DESCRIPTION:
Mapping XS a98b1ec8
END DESCRIPTION:
XS GIS Cut Line= 6
      1616947.13      6845407.63      1616990.10      6845481.84
      1617018.75      6845580.80      1617044.79      6845782.62
      1617069.53      6845798.25      1617730.52      6845799.55
#Sta/Elev= 30
  4675.7 1770.81  4719.0 1769.63  4724.7 1768.43  4788.7 1768.99  4817.9 1767.57
  4818.2 1767.07  4821.7 1767.07  4821.9 1767.57  4834.3 1768.66  4871.7 1768.92
  4961.8 1771.31  5001.9 1770.78  5007.0 1770.06  5012.6 1770.69  5043.4 1770.41
  5048.6 1768.88  5053.8 1770.24  5068.8 1770.27  5072.3 1768.79  5080.9 1770.42
  5098.1 1769.60  5103.6 1770.45  5113.6 1770.72  5153.6 1771.05  5233.6 1773.55
  5293.6 1776.50  5333.6 1776.97  5373.6 1778.79  5653.6 1782.77  5759.1 1785.59
#Mann=3,-1,0
  4675.7    0.05       0  4817.9    0.03       0  4821.9    0.05       0
Bank Sta=4817.9,4821.9
Exp/Cntr=0.3,0.1

Type RM Length L Ch R = 1,1735,307,307,307
BEGIN DESCRIPTION:
Mapping XS c18c4fe7
END DESCRIPTION:
XS GIS Cut Line= 5
      1616941.92      6845421.94      1616983.59      6845722.73
      1617040.88      6845876.37      1617240.10      6846044.34
      1617698.39      6846138.09
#Sta/Elev= 30
  4666.8 1770.59  4864.7 1767.84  4870.6 1767.66  4875.6 1766.37  4915.2 1765.71
  4985.1 1765.24  4990.4 1766.94  5020.8 1767.12  5125.5 1766.81  5134.4 1765.46
  5172.1 1764.26  5172.4 1763.76  5175.9 1763.76  5176.1 1764.26  5195.0 1765.26
  5209.3 1767.32  5217.0 1769.48  5244.5 1772.30  5330.2 1776.09  5351.0 1775.64
  5358.8 1776.62  5393.9 1777.72  5451.1 1778.31  5487.4 1779.43  5563.3 1779.72
  5747.1 1781.79  5777.7 1782.29  5798.1 1783.35  5816.5 1783.30  5862.8 1784.61
#Mann=4,-1,0
  4666.8    0.05       0  5172.1    0.03       0  5176.1    0.05       0
  5816.5    0.12       0
Bank Sta=5172.1,5176.1
Exp/Cntr=0.3,0.1

Type RM Length L Ch R = 1,1428,272,272,272
BEGIN DESCRIPTION:
Elm 02 24 1427.77
END DESCRIPTION:
XS GIS Cut Line= 3
      1616623.76      6845360.80      1616837.31      6845991.02
      1616878.98      6846480.63
#Sta/Elev= 30
  4338.2 1780.54  4599.2 1775.81  4694.2 1773.29  4725.9 1773.29  4831.5 1769.53
  4851.8 1768.17  4863.2 1765.95  4873.7 1764.73  4894.8 1764.08  4951.3 1764.77
  4977.4 1763.62  4982.7 1764.25  5003.6 1763.80  5050.8 1764.31  5090.9 1763.72
  5109.0 1762.79  5109.2 1762.29  5112.7 1762.29  5113.0 1762.79  5141.1 1764.62
  5161.2 1767.03  5171.2 1767.62  5221.4 1769.55  5268.9 1769.82  5273.9 1770.61
  5291.6 1770.77  5331.8 1773.04  5361.9 1772.82  5422.1 1773.89  5495.0 1773.65
#Mann=3,-1,0
  4338.2    0.05       0  5109.0    0.05       0  5113.0    0.05       0
Bank Sta=5109,5113
Exp/Cntr=0.3,0.1

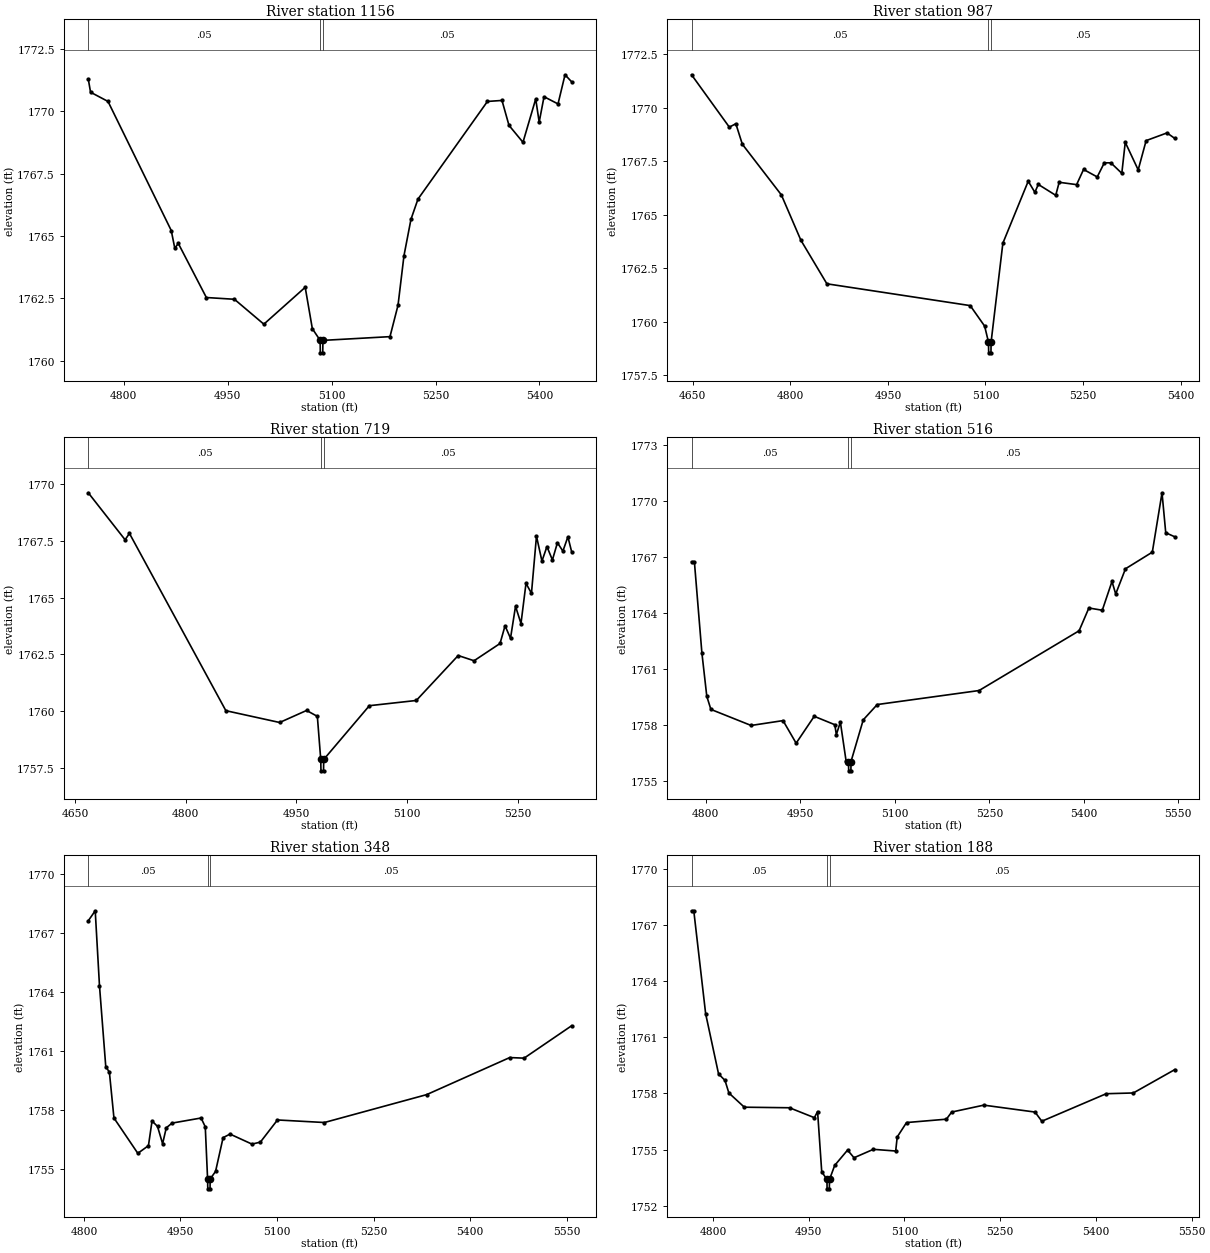
Type RM Length L Ch R = 1,1156,169,169,169
BEGIN DESCRIPTION:
Elm 02 24 1155.55
END DESCRIPTION:
XS GIS Cut Line= 4
      1616620.55      6845789.87      1616578.88      6846039.90
      1616550.23      6846159.69      1616597.11      6846477.40
#Sta/Elev= 30
  4748.6 1771.30  4751.9 1770.77  4777.1 1770.40  4868.4 1765.22  4873.5 1764.51
  4878.6 1764.70  4919.1 1762.53  4959.6 1762.46  5002.1 1761.46  5061.8 1762.94
  5072.1 1761.28  5083.4 1760.81  5083.6 1760.31  5087.1 1760.31  5087.4 1760.81
  5184.2 1760.96  5195.8 1762.22  5204.4 1764.21  5214.5 1765.67  5224.6 1766.48
  5324.9 1770.40  5345.9 1770.44  5356.0 1769.44  5376.2 1768.76  5394.6 1770.50
  5399.6 1769.57  5406.6 1770.59  5426.8 1770.30  5436.9 1771.47  5446.4 1771.19
#Mann=3,-1,0
  4748.6    0.05       0  5083.4    0.05       0  5087.4    0.05       0
Bank Sta=5083.4,5087.4
Exp/Cntr=0.3,0.1

Type RM Length L Ch R = 1,987,268,268,268
BEGIN DESCRIPTION:
Elm 02 24 987.03
END DESCRIPTION:
XS GIS Cut Line= 4
      1616459.08      6845789.92      1616451.27      6846144.06
      1616466.90      6846310.73      1616534.61      6846521.70
#Sta/Elev= 30
  4648.0 1771.55  4706.1 1769.10  4716.1 1769.26  4726.1 1768.30  4786.1 1765.93
  4816.1 1763.81  4856.1 1761.77  5076.5 1760.75  5098.7 1759.79  5104.6 1759.04
  5104.9 1758.54  5108.4 1758.54  5108.6 1759.04  5126.7 1763.67  5165.7 1766.57
  5175.9 1766.05  5181.2 1766.42  5208.0 1765.91  5213.3 1766.52  5240.1 1766.41
  5250.8 1767.12  5271.8 1766.77  5282.7 1767.43  5292.8 1767.43  5309.6 1766.94
  5314.9 1768.39  5334.8 1767.10  5347.0 1768.47  5379.1 1768.83  5391.2 1768.57
#Mann=3,-1,0
  4648.0    0.05       0  5104.6    0.03       0  5108.6    0.05       0
Bank Sta=5104.6,5108.6
Exp/Cntr=0.3,0.1

Type RM Length L Ch R = 1,719,203,203,203
BEGIN DESCRIPTION:
Elm 02 24 718.68
END DESCRIPTION:
XS GIS Cut Line= 3
      1616060.62      6845925.27      1616237.73      6846206.56
      1616453.89      6846446.16
#Sta/Elev= 30
  4668.1 1769.62  4718.0 1767.55  4723.9 1767.83  4854.6 1760.02  4927.5 1759.50
  4964.0 1760.03  4978.6 1759.77  4983.2 1757.87  4983.5 1757.37  4987.0 1757.37
  4987.2 1757.87  5049.1 1760.24  5112.7 1760.47  5169.5 1762.45  5191.0 1762.22
  5226.2 1762.98  5233.0 1763.76  5240.4 1763.21  5247.2 1764.62  5254.6 1763.86
  5261.4 1765.63  5268.8 1765.19  5275.6 1767.71  5283.0 1766.61  5289.8 1767.25
  5297.2 1766.66  5304.0 1767.42  5311.4 1767.05  5318.2 1767.68  5323.2 1767.03
#Mann=3,-1,0
  4668.1    0.05       0  4983.2    0.03       0  4987.2    0.05       0
Bank Sta=4983.2,4987.2
Exp/Cntr=0.3,0.1

Type RM Length L Ch R = 1,516,168,168,168
BEGIN DESCRIPTION:
Elm 02 24 516.23
END DESCRIPTION:
XS GIS Cut Line= 3
      1615933.04      6846196.15      1616107.52      6846341.98
      1616568.23      6846623.09
#Sta/Elev= 30
  4777.4 1766.76  4781.9 1766.76  4793.8 1761.88  4801.6 1759.55  4808.1 1758.85
  4871.9 1757.99  4922.6 1758.25  4943.4 1757.04  4972.1 1758.48  5004.8 1758.03
  5007.2 1757.50  5013.6 1758.17  5022.7 1756.08  5026.5 1756.06  5026.8 1755.56
  5030.3 1755.56  5030.5 1756.06  5049.9 1758.29  5072.1 1759.11  5233.7 1759.86
  5392.5 1763.06  5408.0 1764.28  5429.3 1764.16  5444.7 1765.70  5450.6 1765.03
  5466.1 1766.38  5508.7 1767.27  5524.1 1770.45  5530.0 1768.31  5544.5 1768.09
#Mann=3,-1,0
  4777.4    0.05       0  5026.5    0.03       0  5030.5    0.05       0
Bank Sta=5026.5,5030.5
Exp/Cntr=0.3,0.1

Type RM Length L Ch R = 1,348,160,160,160
BEGIN DESCRIPTION:
Mapping XS a9dff50f
END DESCRIPTION:
XS GIS Cut Line= 4
      1615865.47      6846222.61      1615989.19      6846459.62
      1616271.74      6846531.24      1616443.61      6846617.17
#Sta/Elev= 30
  4806.8 1767.64  4817.6 1768.15  4824.2 1764.34  4834.0 1760.20  4839.6 1759.93
  4846.7 1757.59  4883.8 1755.79  4900.3 1756.18  4905.9 1757.44  4914.4 1757.16
  4922.3 1756.28  4928.0 1757.09  4937.0 1757.33  4982.1 1757.59  4988.6 1757.14
  4992.2 1754.48  4992.5 1753.98  4996.0 1753.98  4996.2 1754.48  5004.6 1754.87
  5016.3 1756.59  5027.1 1756.77  5061.1 1756.26  5074.2 1756.36  5100.8 1757.49
  5173.7 1757.36  5332.5 1758.78  5461.7 1760.67  5484.0 1760.64  5557.8 1762.29
#Mann=3,-1,0
  4806.8    0.05       0  4992.2    0.03       0  4996.2    0.05       0
Bank Sta=4992.2,4996.2
Exp/Cntr=0.3,0.1

Type RM Length L Ch R = 1,188,0,0,0
BEGIN DESCRIPTION:
Elm 02 24 475.123
END DESCRIPTION:
XS GIS Cut Line= 3
      1615791.27      6846186.15      1615838.15      6846502.59
      1616271.57      6846562.28
#Sta/Elev= 30
  4766.3 1767.75  4769.8 1767.75  4788.4 1762.25  4808.6 1759.04  4818.7 1758.69
  4824.8 1758.02  4849.0 1757.26  4919.8 1757.23  4958.8 1756.70  4963.8 1757.03
  4970.3 1753.81  4978.5 1753.40  4978.7 1752.90  4982.2 1752.90  4982.5 1753.40
  4990.6 1754.15  5010.8 1754.97  5020.9 1754.56  5051.2 1755.01  5086.2 1754.92
  5088.6 1755.67  5103.2 1756.44  5165.7 1756.62  5173.9 1757.00  5224.3 1757.37
  5304.6 1757.00  5315.2 1756.51  5416.1 1757.98  5458.6 1758.02  5523.7 1759.27
#Mann=3,-1,0
  4766.3    0.05       0  4978.5    0.05       0  4982.5    0.05       0
Bank Sta=4978.5,4982.5
Exp/Cntr=0.3,0.1

Chan Stop Cuts=-1