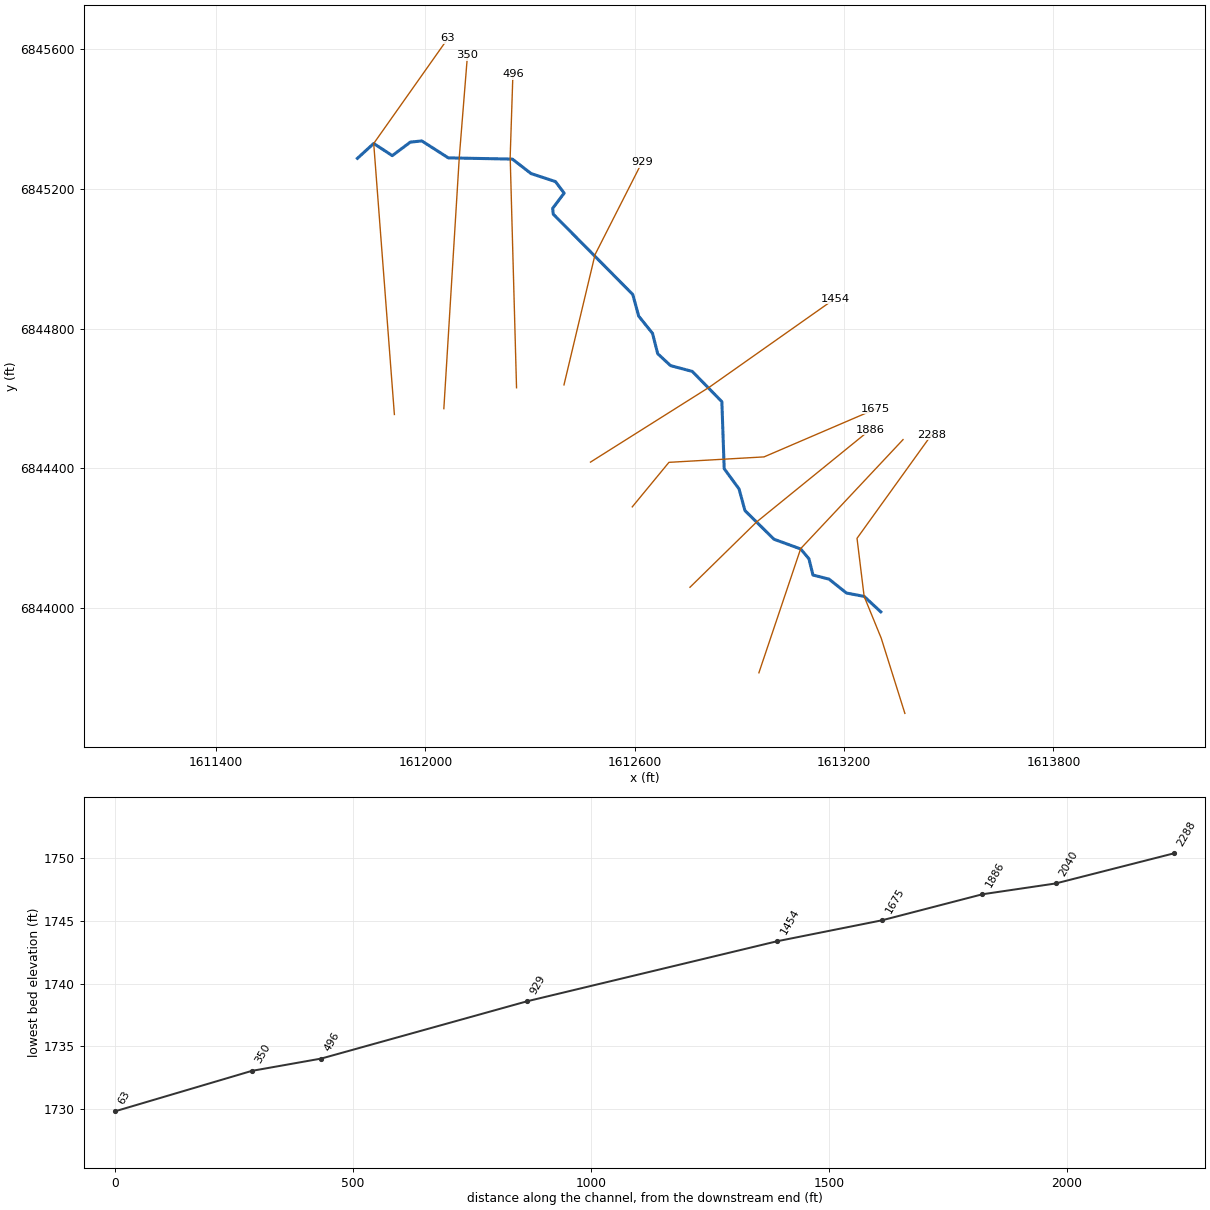
--- Elm 02 25.prj (project) ---

Proj Title=Elm 02 25 Base Level Engineering
Current Plan=p01
Default Exp/Contr=0.3,0.1
English Units
Geom File=g01
Flow File=f01
Plan File=p01
BEGIN DESCRIPTION:
Elm 02 25
END DESCRIPTION:

--- Elm 02 25.p01 (plan) ---

Plan Title=Multiple Run
Short Identifier=Multiple
Geom File=g01
Flow File=f01
Subcritical Flow
K Sum by GR= 0
Std Step Tol= 0.01
Critical Tol= 0.01
Num of Std Step Trials= 20
Max Error Tol= 0.3
Flow Tol Ratio= 0.001
Split Flow NTrial= 30
Split Flow Tol= 0.02
Split Flow Ratio= 0.02
Log Output Level= 0
Friction Slope Method= 1
Unsteady Friction Slope Method= 2
Unsteady Bridges Friction Slope Method= 1
Parabolic Critical Depth
Global Vel Dist=  1 , 1 , 1
Global Log Level= 0
CheckData=True
Encroach Param= -1, 0, 0, 0
BEGIN DESCRIPTION:
Multiple Run
END DESCRIPTION:

--- Elm 02 25.f01 (steady flow) ---

Flow Title=Multiple
Number of Profiles=7
Profile Names=10-year,25-year,50-year,1pct_min,100-year,1pct_plu,500-year
River Rch & RM= Elm 02 25,Reach-1,2288
     107     140     166     122     196     270     276
Boundary for River Rch & Prof#=Elm 02 25,Reach-1,1
Up Type=0
Dn Type=3
Dn Slope=0.001
Boundary for River Rch & Prof#=Elm 02 25,Reach-1,2
Up Type=0
Dn Type=3
Dn Slope=0.001
Boundary for River Rch & Prof#=Elm 02 25,Reach-1,3
Up Type=0
Dn Type=3
Dn Slope=0.001
Boundary for River Rch & Prof#=Elm 02 25,Reach-1,4
Up Type=0
Dn Type=3
Dn Slope=0.001
Boundary for River Rch & Prof#=Elm 02 25,Reach-1,5
Up Type=0
Dn Type=3
Dn Slope=0.001
Boundary for River Rch & Prof#=Elm 02 25,Reach-1,6
Up Type=0
Dn Type=3
Dn Slope=0.001
Boundary for River Rch & Prof#=Elm 02 25,Reach-1,7
Up Type=0
Dn Type=3
Dn Slope=0.001

--- Elm 02 25.g01 (geometry) ---

Geom Title=Existing Conditions

River Reach=Elm 02 25,Reach-1
Reach XY= 30
      1613305.00      6843988.00      1613257.36      6844032.32
      1613206.64      6844042.03      1613156.86      6844081.77
      1613110.62      6844093.62      1613099.11      6844140.20
      1613075.43      6844168.27      1612998.95      6844196.16
      1612915.75      6844278.29      1612898.86      6844340.17
      1612856.20      6844398.50      1612849.55      6844590.47
      1612764.69      6844677.22      1612702.46      6844693.75
      1612665.63      6844728.00      1612650.80      6844786.24
      1612611.10      6844835.81      1612594.24      6844897.68
      1612366.25      6845128.01      1612364.62      6845144.68
      1612397.53      6845188.21      1612372.53      6845221.36
      1612302.88      6845244.14      1612249.07      6845285.76
      1612065.50      6845289.24      1611989.58      6845337.85
      1611956.63      6845334.41      1611904.91      6845295.67
      1611851.66      6845330.49      1611805.00      6845288.00

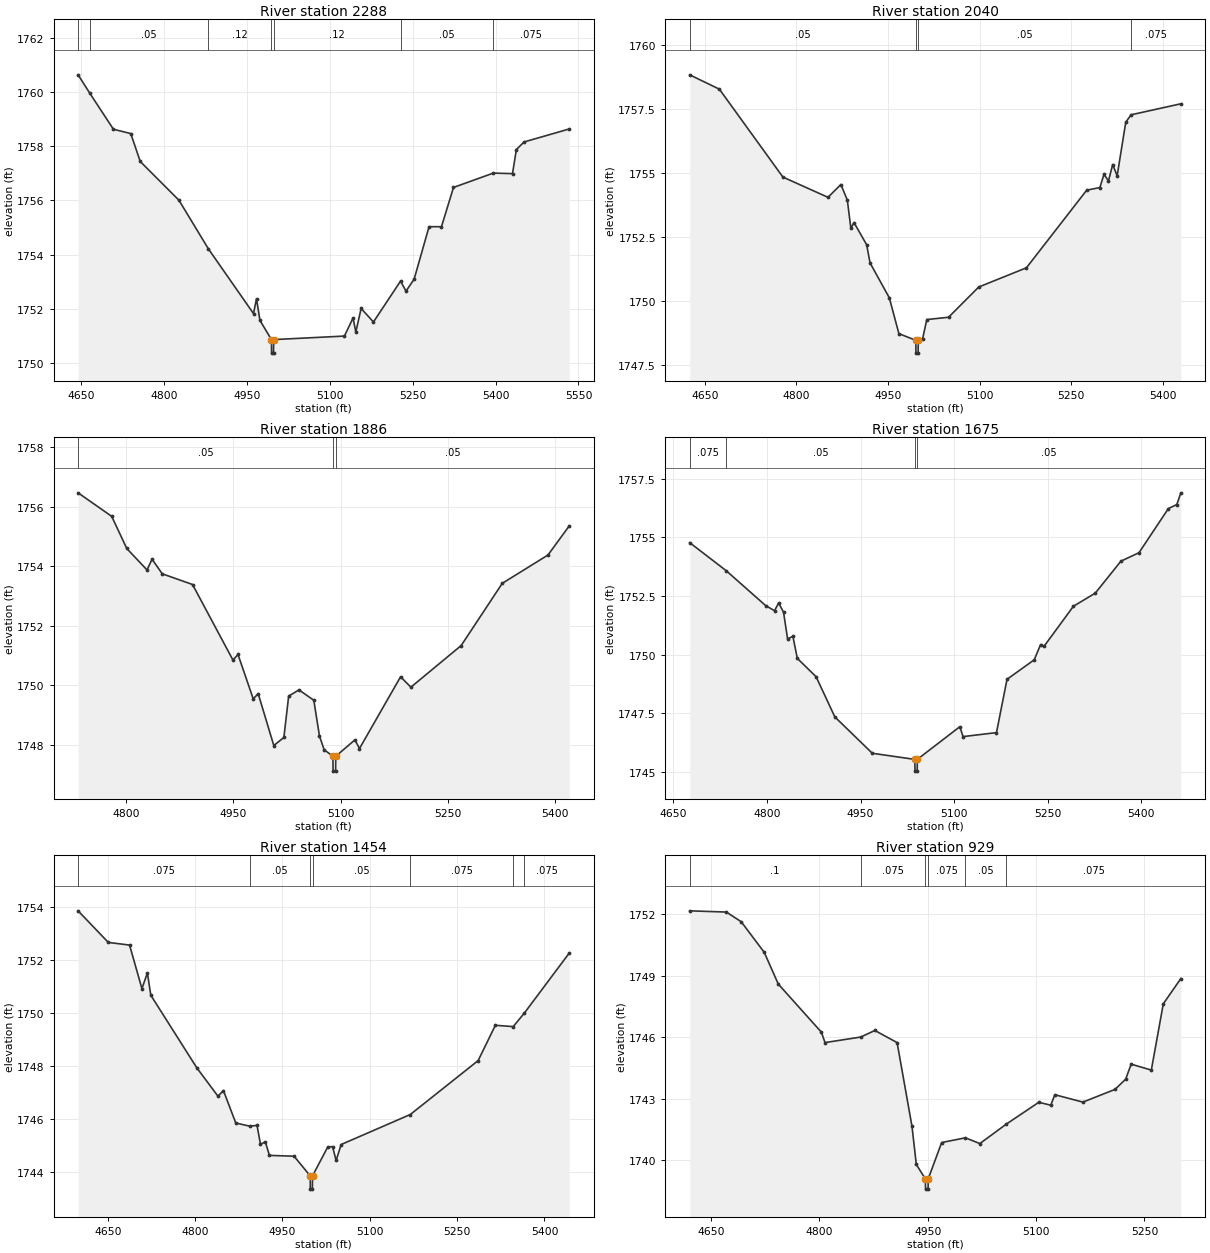
Type RM Length L Ch R = 1,2288,248,248,248
BEGIN DESCRIPTION:
Elm 02 25 1970.044
END DESCRIPTION:
XS GIS Cut Line= 5
      1613374.10      6843697.05      1613306.39      6843912.32
      1613257.36      6844032.32      1613236.95      6844198.78
      1613450.49      6844495.65
#Sta/Elev= 30
  4644.7 1760.64  4665.9 1759.96  4708.6 1758.63  4740.0 1758.47  4757.1 1757.44
  4827.1 1756.01  4880.5 1754.21  4962.1 1751.82  4967.5 1752.37  4973.7 1751.57
  4994.5 1750.86  4994.8 1750.36  4998.3 1750.36  4998.5 1750.86  5126.6 1750.99
  5142.2 1751.66  5147.2 1751.14  5156.8 1752.01  5179.1 1751.51  5228.1 1753.02
  5238.0 1752.65  5252.7 1753.09  5279.7 1755.03  5302.2 1755.03  5323.9 1756.48
  5396.0 1757.01  5430.7 1756.99  5437.7 1757.88  5451.6 1758.16  5533.4 1758.64
#Mann=7,-1,0
  4644.7   0.075       0  4665.9    0.05       0  4880.5    0.12       0
  4994.5    0.07       0  4998.5    0.12       0  5228.1    0.05       0
  5396.0   0.075       0
Bank Sta=4994.5,4998.5
Exp/Cntr=0.3,0.1

Type RM Length L Ch R = 1,2040,154,154,154
BEGIN DESCRIPTION:
Elm 02 25 2039.73
END DESCRIPTION:
XS GIS Cut Line= 3
      1612955.71      6843813.40      1613075.49      6844169.26
      1613368.87      6844481.74
#Sta/Elev= 30
  4625.4 1758.83  4674.0 1758.27  4778.0 1754.84  4851.8 1754.05  4872.9 1754.55
  4883.5 1753.94  4889.2 1752.85  4894.5 1753.06  4915.1 1752.20  4920.7 1751.49
  4952.2 1750.13  4967.9 1748.73  4995.6 1748.47  4995.8 1747.97  4999.3 1747.97
  4999.6 1748.47  5006.7 1748.53  5013.6 1749.28  5049.2 1749.37  5098.6 1750.55
  5176.7 1751.30  5275.4 1754.33  5296.9 1754.43  5303.7 1754.95  5311.0 1754.69
  5317.9 1755.33  5325.2 1754.89  5339.3 1756.98  5348.0 1757.27  5429.5 1757.70
#Mann=4,-1,0
  4625.4    0.05       0  4995.6    0.05       0  4999.6    0.05       0
  5348.0   0.075       0
Bank Sta=4995.6,4999.6
Exp/Cntr=0.3,0.1

Type RM Length L Ch R = 1,1886,211,211,211
BEGIN DESCRIPTION:
Elm 02 25 1886.49
END DESCRIPTION:
XS GIS Cut Line= 3
      1612758.12      6844058.49      1612949.51      6844245.98
      1613275.00      6844510.28
#Sta/Elev= 30
  4732.8 1756.46  4779.8 1755.67  4800.9 1754.59  4829.2 1753.87  4836.3 1754.23
  4850.5 1753.74  4892.9 1753.38  4949.5 1750.84  4956.5 1751.03  4977.8 1749.54
  4984.8 1749.71  5006.6 1747.97  5020.7 1748.24  5027.4 1749.63  5041.8 1749.84
  5062.6 1749.49  5070.5 1748.29  5077.0 1747.83  5089.3 1747.61  5089.6 1747.11
  5093.1 1747.11  5093.3 1747.61  5120.1 1748.16  5126.5 1747.87  5184.0 1750.28
  5198.4 1749.93  5268.8 1751.33  5326.3 1753.42  5390.2 1754.37  5420.0 1755.35
#Mann=3,-1,0
  4732.8    0.05       0  5089.3    0.05       0  5093.3    0.05       0
Bank Sta=5089.3,5093.3
Exp/Cntr=0.3,0.1

Type RM Length L Ch R = 1,1675,221,221,221
BEGIN DESCRIPTION:
Elm 02 25 1700.33
END DESCRIPTION:
XS GIS Cut Line= 4
      1612592.73      6844288.93      1612697.87      6844416.57
      1612970.44      6844432.19      1613290.98      6844569.78
#Sta/Elev= 30
  4676.2 1754.77  4734.9 1753.57  4797.9 1752.09  4812.2 1751.87  4818.7 1752.20
  4826.6 1751.81  4833.1 1750.67  4841.6 1750.78  4848.7 1749.84  4878.8 1749.06
  4908.8 1747.35  4968.9 1745.80  5037.0 1745.54  5037.3 1745.04  5040.8 1745.04
  5041.0 1745.54  5109.1 1746.93  5114.4 1746.51  5167.9 1746.68  5184.8 1748.95
  5228.4 1749.78  5238.6 1750.43  5244.0 1750.35  5291.2 1752.06  5326.3 1752.62
  5367.3 1753.98  5396.3 1754.34  5443.4 1756.22  5456.9 1756.39  5463.4 1756.89
#Mann=4,-1,0
  4676.2   0.075       0  4734.9    0.05       0  5037.0    0.03       0
  5041.0    0.05       0
Bank Sta=5037,5041
Exp/Cntr=0.3,0.1

Type RM Length L Ch R = 1,1454,525,525,525
BEGIN DESCRIPTION:
Elm 02 25 1454.24
END DESCRIPTION:
XS GIS Cut Line= 3
      1612473.00      6844417.25      1612813.71      6844632.09
      1613173.94      6844885.99
#Sta/Elev= 30
  4599.1 1753.85  4651.0 1752.66  4687.5 1752.56  4708.7 1750.92  4718.1 1751.51
  4724.0 1750.67  4802.9 1747.94  4839.3 1746.87  4848.7 1747.08  4869.9 1745.86
  4893.9 1745.74  4906.4 1745.77  4912.3 1745.06  4920.7 1745.15  4927.6 1744.64
  4970.0 1744.61  4997.7 1743.87  4997.9 1743.37  5001.4 1743.37  5001.7 1743.87
  5027.9 1744.96  5036.1 1744.97  5042.2 1744.45  5050.9 1745.05  5169.6 1746.18
  5286.1 1748.21  5315.7 1749.54  5346.3 1749.49  5365.5 1750.00  5442.6 1752.26
#Mann=7,-1,0
  4599.1   0.075       0  4893.9    0.05       0  4997.7    0.05       0
  5001.7    0.05       0  5169.6   0.075       0  5346.3    0.05       0
  5365.5   0.075       0
Bank Sta=4997.7,5001.7
Exp/Cntr=0.3,0.1

Type RM Length L Ch R = 1,929,433,433,433
BEGIN DESCRIPTION:
Elm 02 25 928.51
END DESCRIPTION:
XS GIS Cut Line= 3
      1612397.04      6844638.60      1612486.01      6845011.86
      1612620.29      6845276.08
#Sta/Elev= 30
  4620.3 1752.16  4671.1 1752.10  4691.6 1751.63  4723.5 1750.14  4743.0 1748.59
  4802.6 1746.25  4807.7 1745.74  4857.1 1746.01  4876.7 1746.33  4907.5 1745.74
  4928.1 1741.66  4934.1 1739.80  4946.6 1739.10  4946.9 1738.60  4950.4 1738.60
  4950.6 1739.10  4969.2 1740.87  5002.0 1741.10  5022.1 1740.82  5058.8 1741.77
  5103.7 1742.83  5120.3 1742.69  5125.9 1743.20  5164.8 1742.84  5209.3 1743.46
  5224.0 1743.96  5231.6 1744.69  5259.5 1744.40  5276.1 1747.63  5300.4 1748.86
#Mann=6,-1,0
  4620.3     0.1       0  4857.1   0.075       0  4946.6    0.07       0
  4950.6   0.075       0  5002.0    0.05       0  5058.8   0.075       0
Bank Sta=4946.6,4950.6
Exp/Cntr=0.3,0.1

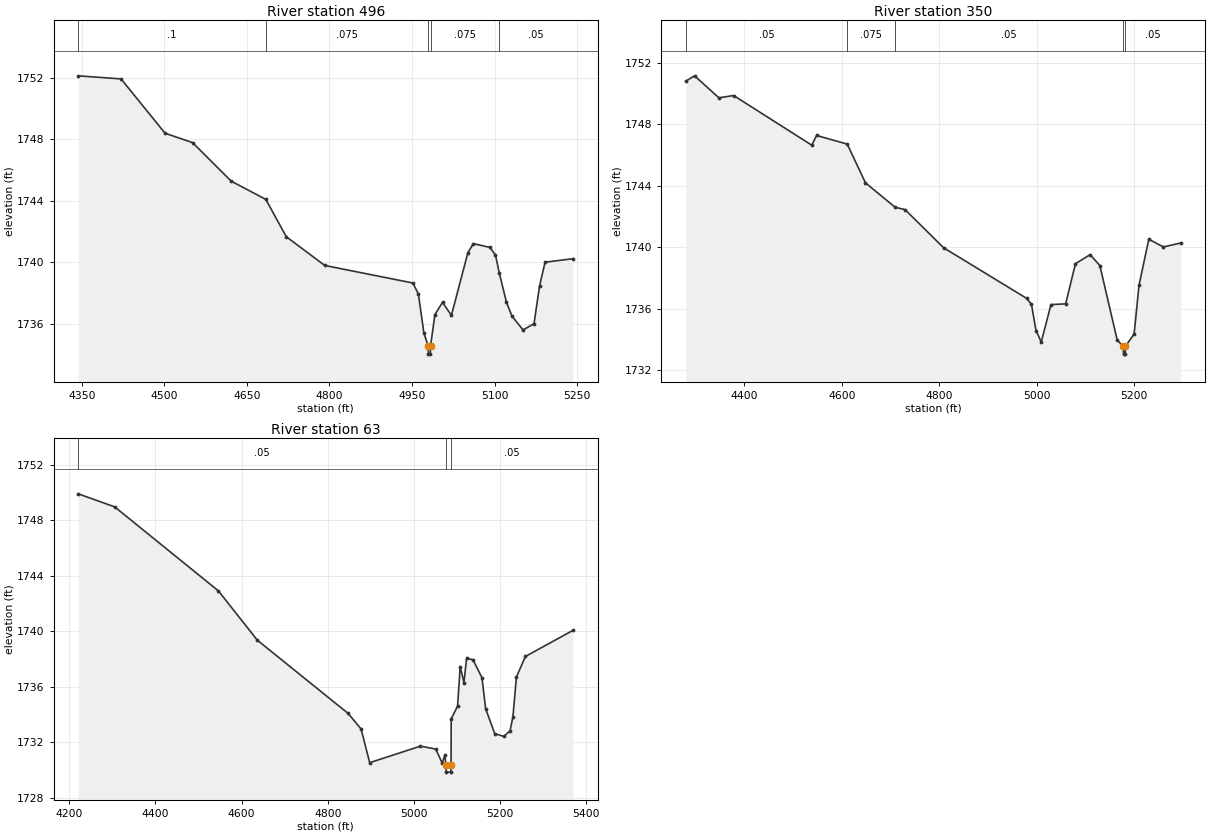
Type RM Length L Ch R = 1,496,146,146,146
BEGIN DESCRIPTION:
Elm 02 25 495.84
END DESCRIPTION:
XS GIS Cut Line= 3
      1612261.04      6844630.38      1612242.81      6845291.81
      1612250.62      6845528.80
#Sta/Elev= 30
  4343.7 1752.12  4421.4 1751.92  4501.4 1748.39  4551.4 1747.78  4621.4 1745.28
  4684.5 1744.09  4721.5 1741.67  4791.5 1739.80  4951.6 1738.66  4961.6 1737.95
  4971.6 1735.41  4979.6 1734.54  4979.8 1734.04  4983.3 1734.04  4983.6 1734.54
  4991.6 1736.61  5005.4 1737.40  5021.6 1736.56  5051.6 1740.64  5061.6 1741.22
  5091.6 1740.97  5101.6 1740.48  5108.7 1739.29  5121.6 1737.41  5131.6 1736.51
  5151.7 1735.61  5171.7 1736.02  5181.7 1738.47  5191.7 1740.01  5242.5 1740.24
#Mann=5,-1,0
  4343.7     0.1       0  4684.5   0.075       0  4979.6    0.07       0
  4983.6   0.075       0  5108.7    0.05       0
Bank Sta=4979.6,4983.6
Exp/Cntr=0.3,0.1

Type RM Length L Ch R = 1,350,287,287,287
BEGIN DESCRIPTION:
Elm 02 25 349.58
END DESCRIPTION:
XS GIS Cut Line= 3
      1612052.70      6844570.42      1612096.97      6845291.81
      1612120.39      6845583.22
#Sta/Elev= 30
  4280.0 1750.82  4297.6 1751.16  4347.7 1749.73  4377.8 1749.88  4538.1 1746.65
  4548.1 1747.28  4611.0 1746.72  4648.3 1744.20  4709.3 1742.61  4729.5 1742.46
  4808.6 1739.98  4978.9 1736.69  4988.9 1736.30  4998.3 1734.59  5009.0 1733.85
  5029.0 1736.28  5059.1 1736.33  5079.2 1738.94  5109.3 1739.53  5129.3 1738.82
  5164.9 1733.97  5177.5 1733.56  5177.8 1733.06  5181.3 1733.06  5181.5 1733.56
  5199.6 1734.37  5209.6 1737.54  5229.7 1740.53  5259.8 1740.03  5295.1 1740.29
#Mann=5,-1,0
  4280.0    0.05       0  4611.0   0.075       0  4709.3    0.05       0
  5177.5    0.03       0  5181.5    0.05       0
Bank Sta=5177.5,5181.5
Exp/Cntr=0.3,0.1

Type RM Length L Ch R = 1,63,0,0,0
BEGIN DESCRIPTION:
Elm 02 25 519.787
END DESCRIPTION:
XS GIS Cut Line= 3
      1611910.91      6844553.75      1611851.66      6845330.49
      1612064.54      6845631.89
#Sta/Elev= 30
  4221.0 1749.89  4305.5 1748.95  4546.2 1742.90  4636.5 1739.35  4847.1 1734.08
  4877.2 1732.96  4897.2 1730.53  5014.9 1731.72  5050.6 1731.51  5065.4 1730.50
  5071.5 1731.06  5074.3 1730.35  5074.8 1729.85  5085.5 1729.85  5086.0 1730.35
  5086.3 1733.68  5101.1 1734.60  5107.2 1737.45  5115.9 1736.30  5122.0 1738.04
  5136.8 1737.95  5157.7 1736.65  5166.3 1734.41  5187.3 1732.63  5208.2 1732.42
  5222.9 1732.82  5229.6 1733.84  5237.7 1736.70  5258.6 1738.18  5369.0 1740.06
#Mann=3,-1,0
  4221.0    0.05       0  5074.3    0.03       0  5086.0    0.05       0
Bank Sta=5074.3,5086
Exp/Cntr=0.3,0.1

Chan Stop Cuts=-1