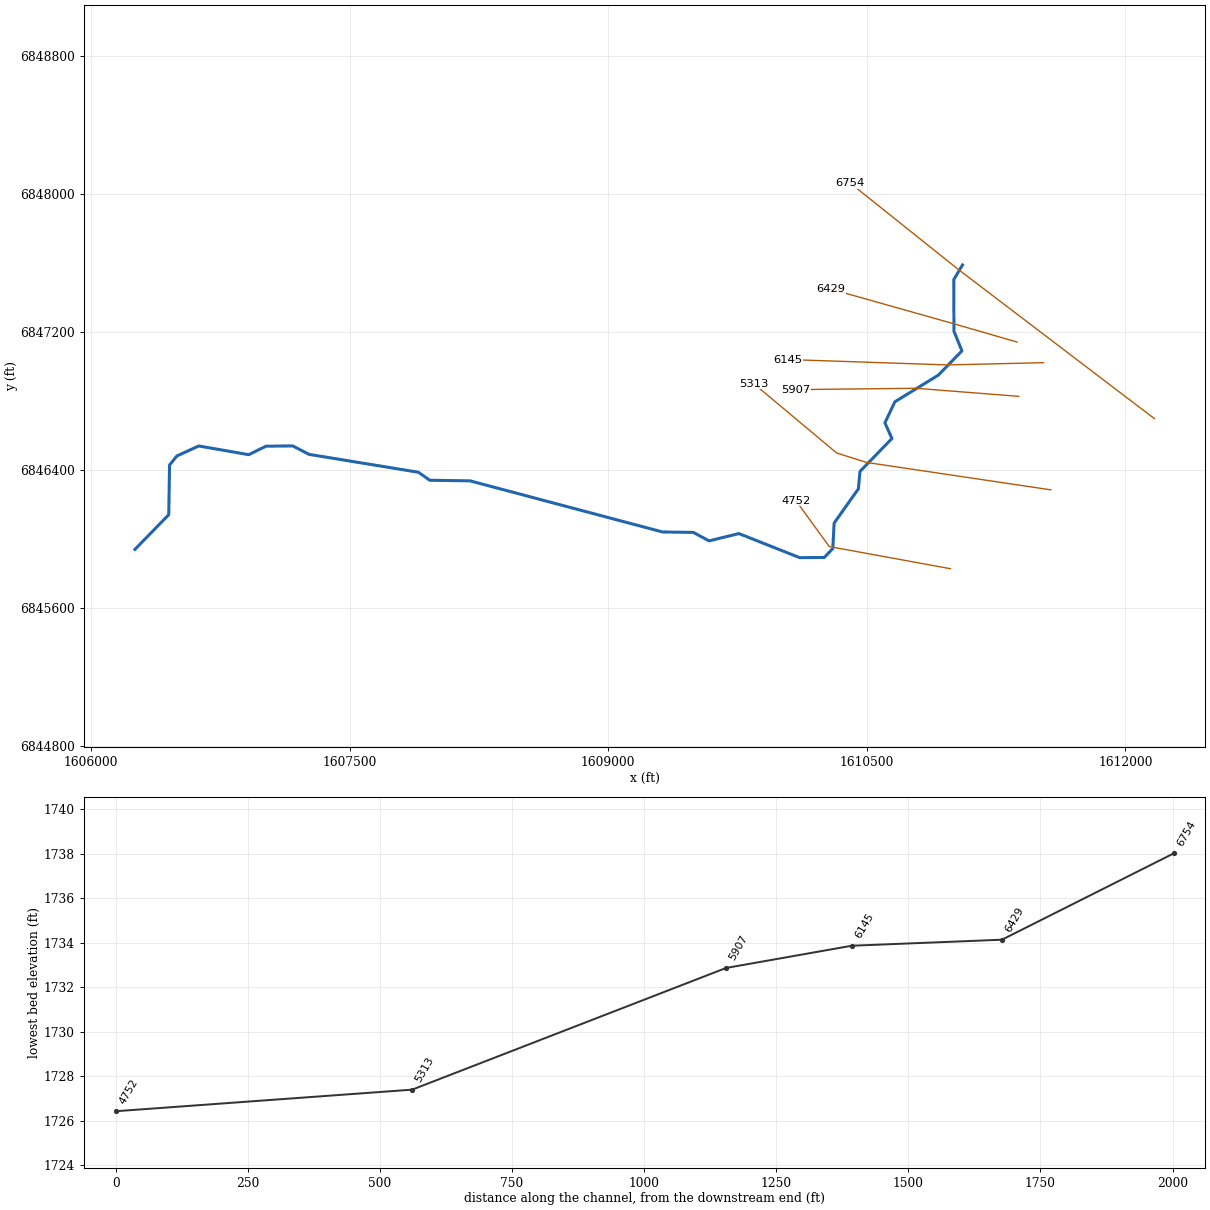
--- Elm 02 26.prj (project) ---

Proj Title=Elm 02 26 Base Level Engineering
Current Plan=p01
Default Exp/Contr=0.3,0.1
English Units
Geom File=g01
Flow File=f01
Plan File=p01
BEGIN DESCRIPTION:
Elm 02 26
END DESCRIPTION:

--- Elm 02 26.p01 (plan) ---

Plan Title=Multiple Run
Short Identifier=Multiple
Geom File=g01
Flow File=f01
Subcritical Flow
K Sum by GR= 0
Std Step Tol= 0.01
Critical Tol= 0.01
Num of Std Step Trials= 20
Max Error Tol= 0.3
Flow Tol Ratio= 0.001
Split Flow NTrial= 30
Split Flow Tol= 0.02
Split Flow Ratio= 0.02
Log Output Level= 0
Friction Slope Method= 1
Unsteady Friction Slope Method= 2
Unsteady Bridges Friction Slope Method= 1
Parabolic Critical Depth
Global Vel Dist=  1 , 1 , 1
Global Log Level= 0
CheckData=True
Encroach Param= -1, 0, 0, 0
BEGIN DESCRIPTION:
Multiple Run
END DESCRIPTION:

--- Elm 02 26.f01 (steady flow) ---

Flow Title=Multiple
Number of Profiles=7
Profile Names=10-year,25-year,50-year,1pct_min,100-year,1pct_plu,500-year
River Rch & RM= Elm 02 26,Reach-1,6754
      98     126     148     107     172     237     236
Boundary for River Rch & Prof#=Elm 02 26,Reach-1,1
Up Type=0
Dn Type=3
Dn Slope=0.001
Boundary for River Rch & Prof#=Elm 02 26,Reach-1,2
Up Type=0
Dn Type=3
Dn Slope=0.001
Boundary for River Rch & Prof#=Elm 02 26,Reach-1,3
Up Type=0
Dn Type=3
Dn Slope=0.001
Boundary for River Rch & Prof#=Elm 02 26,Reach-1,4
Up Type=0
Dn Type=3
Dn Slope=0.001
Boundary for River Rch & Prof#=Elm 02 26,Reach-1,5
Up Type=0
Dn Type=3
Dn Slope=0.001
Boundary for River Rch & Prof#=Elm 02 26,Reach-1,6
Up Type=0
Dn Type=3
Dn Slope=0.001
Boundary for River Rch & Prof#=Elm 02 26,Reach-1,7
Up Type=0
Dn Type=3
Dn Slope=0.001

--- Elm 02 26.g01 (geometry) ---

Geom Title=Existing Conditions

River Reach=Elm 02 26,Reach-1
Reach XY= 30
      1611055.00      6847588.00      1611004.59      6847503.17
      1611005.54      6847203.21      1611051.87      6847089.63
      1610914.68      6846948.78      1610663.02      6846794.34
      1610605.14      6846672.59      1610645.85      6846581.27
      1610460.52      6846390.43      1610451.17      6846289.59
      1610310.48      6846090.44      1610303.02      6845943.65
      1610253.78      6845891.43      1610110.94      6845890.25
      1609758.30      6846029.92      1609584.87      6845987.61
      1609494.49      6846036.78      1609315.51      6846039.22
      1608199.06      6846335.74      1607965.50      6846339.22
      1607899.06      6846385.73      1607265.50      6846489.22
      1607170.18      6846538.43      1607015.51      6846536.78
      1606915.18      6846487.54      1606625.09      6846538.11
      1606498.61      6846480.00      1606455.98      6846427.72
      1606451.46      6846139.46      1606255.00      6845938.00

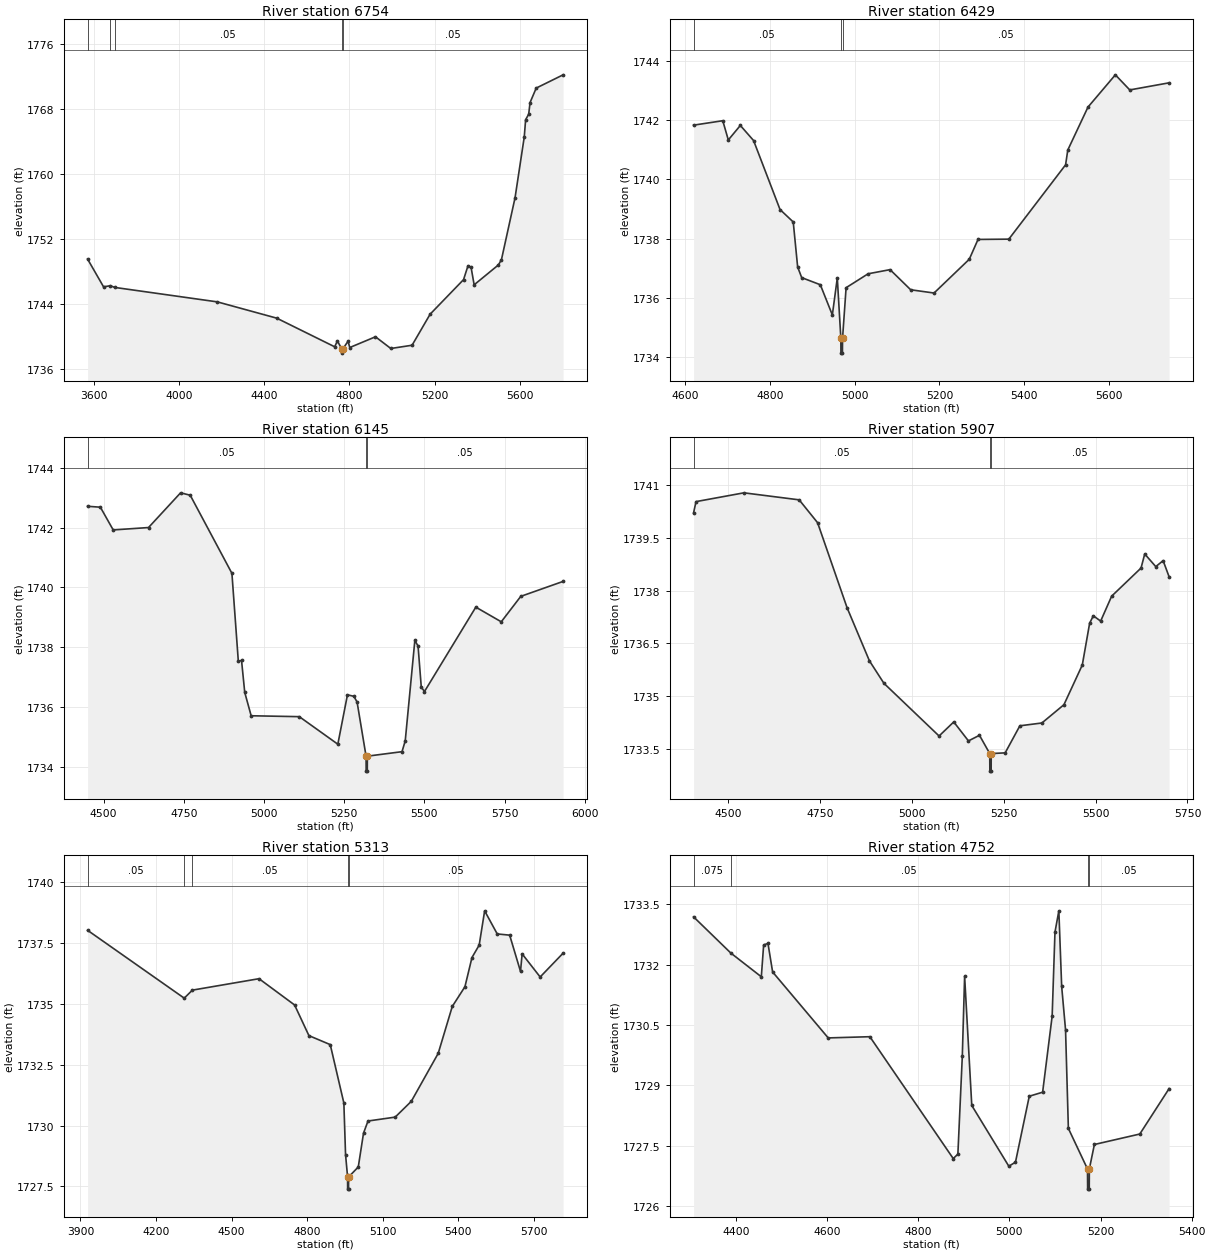
Type RM Length L Ch R = 1,6754,325,325,325
BEGIN DESCRIPTION:
Elm 02 26 6486.054
END DESCRIPTION:
XS GIS Cut Line= 3
      1612168.35      6846696.46      1611030.53      6847562.13
      1610403.13      6848063.32
#Sta/Elev= 30
  3570.3 1749.58  3645.4 1746.16  3677.7 1746.30  3697.6 1746.09  4179.8 1744.31
  4458.4 1742.31  4730.5 1738.79  4743.3 1739.51  4764.1 1738.51  4764.3 1738.01
  4768.1 1738.51  4793.3 1739.47  4801.4 1738.70  4922.1 1740.02  4994.0 1738.58
  5093.9 1738.98  5178.7 1742.80  5335.6 1747.05  5356.5 1748.76  5370.9 1748.56
  5385.3 1746.41  5499.0 1748.85  5513.4 1749.49  5577.4 1757.12  5620.6 1764.59
  5627.0 1766.71  5641.4 1767.39  5647.8 1768.82  5676.7 1770.60  5803.0 1772.23
#Mann=5,-1,0
  3570.3     0.1       0  3677.7   0.075       0  3697.6    0.05       0
  4764.1    0.03       0  4768.1    0.05       0
Bank Sta=4764.1,4768.1
Exp/Cntr=0.3,0.1

Type RM Length L Ch R = 1,6429,284,284,284
BEGIN DESCRIPTION:
Elm 02 26 6429.41
END DESCRIPTION:
XS GIS Cut Line= 3
      1611371.26      6847140.92      1611001.43      6847247.70
      1610290.50      6847448.22
#Sta/Elev= 30
  4619.2 1741.83  4688.2 1741.98  4701.3 1741.33  4729.7 1741.82  4761.0 1741.31
  4823.5 1738.98  4854.7 1738.56  4865.1 1737.04  4874.7 1736.68  4918.7 1736.44
  4947.1 1735.42  4958.8 1736.67  4967.2 1734.63  4967.4 1734.13  4970.9 1734.13
  4971.2 1734.63  4979.6 1736.34  5031.6 1736.81  5083.5 1736.95  5132.2 1736.27
  5187.4 1736.16  5270.6 1737.30  5291.3 1737.97  5364.1 1737.98  5498.2 1740.49
  5503.4 1740.99  5551.1 1742.44  5615.8 1743.53  5649.8 1743.02  5742.8 1743.26
#Mann=3,-1,0
  4619.2    0.05       0  4967.2    0.05       0  4971.2    0.05       0
Bank Sta=4967.2,4971.2
Exp/Cntr=0.3,0.1

Type RM Length L Ch R = 1,6145,238,238,238
BEGIN DESCRIPTION:
Elm 02 26 6144.51
END DESCRIPTION:
XS GIS Cut Line= 3
      1611524.90      6847021.14      1610967.58      6847008.12
      1610043.08      6847039.37
#Sta/Elev= 30
  4450.1 1742.71  4490.0 1742.68  4530.0 1741.92  4640.1 1742.00  4740.1 1743.16
  4770.1 1743.08  4900.1 1740.47  4920.1 1737.53  4930.1 1737.56  4940.1 1736.49
  4960.1 1735.71  5110.2 1735.68  5230.3 1734.76  5260.3 1736.41  5280.3 1736.36
  5290.3 1736.17  5318.3 1734.36  5318.6 1733.86  5322.1 1733.86  5322.3 1734.36
  5430.4 1734.51  5440.4 1734.87  5470.4 1738.23  5480.4 1738.04  5490.4 1736.67
  5500.4 1736.52  5660.5 1739.34  5739.8 1738.85  5800.6 1739.70  5932.6 1740.20
#Mann=3,-1,0
  4450.1    0.05       0  5318.3    0.03       0  5322.3    0.05       0
Bank Sta=5318.3,5322.3
Exp/Cntr=0.3,0.1

Type RM Length L Ch R = 1,5907,594,594,594
BEGIN DESCRIPTION:
Elm 02 26 5907.21
END DESCRIPTION:
XS GIS Cut Line= 3
      1611381.67      6846825.83      1610785.29      6846872.70
      1610088.65      6846864.90
#Sta/Elev= 30
  4405.1 1740.21  4411.8 1740.53  4542.2 1740.78  4692.7 1740.58  4742.8 1739.93
  4823.1 1737.51  4883.9 1736.00  4923.4 1735.36  5073.6 1733.86  5113.6 1734.26
  5153.6 1733.72  5183.6 1733.88  5211.6 1733.36  5211.9 1732.86  5215.4 1732.86
  5215.6 1733.36  5253.6 1733.38  5293.6 1734.15  5353.6 1734.23  5413.6 1734.75
  5463.6 1735.88  5483.6 1737.07  5493.6 1737.28  5513.6 1737.13  5543.6 1737.84
  5623.6 1738.64  5633.6 1739.04  5663.7 1738.68  5683.7 1738.85  5700.0 1738.39
#Mann=3,-1,0
  4405.1    0.05       0  5211.6    0.05       0  5215.6    0.05       0
Bank Sta=5211.6,5215.6
Exp/Cntr=0.3,0.1

Type RM Length L Ch R = 1,5313,561,561,561
BEGIN DESCRIPTION:
Elm 02 26 5313.23
END DESCRIPTION:
XS GIS Cut Line= 4
      1611567.63      6846283.55      1610499.90      6846442.41
      1610325.42      6846497.10      1609846.24      6846898.15
#Sta/Elev= 30
  3928.6 1738.03  4312.2 1735.24  4344.5 1735.57  4609.0 1736.04  4750.2 1734.96
  4807.0 1733.70  4891.7 1733.33  4945.7 1730.93  4952.4 1728.81  4960.5 1727.89
  4960.7 1727.39  4964.2 1727.39  4964.5 1727.89  5002.9 1728.30  5023.7 1729.69
  5041.5 1730.19  5149.4 1730.35  5213.4 1731.00  5320.1 1732.97  5376.0 1734.90
  5426.2 1735.71  5454.1 1736.91  5482.7 1737.42  5504.4 1738.83  5554.3 1737.88
  5603.7 1737.83  5646.7 1736.34  5653.2 1737.06  5724.7 1736.11  5815.8 1737.09
#Mann=5,-1,0
  3928.6    0.05       0  4312.2   0.075       0  4344.5    0.05       0
  4960.5    0.03       0  4964.5    0.05       0
Bank Sta=4960.5,4964.5
Exp/Cntr=0.3,0.1

Type RM Length L Ch R = 1,4752,0,0,0
BEGIN DESCRIPTION:
Elm 02 26 4671.933
END DESCRIPTION:
XS GIS Cut Line= 3
      1610985.64      6845826.14      1610282.51      6845954.62
      1610089.04      6846220.63
#Sta/Elev= 30
  4306.8 1733.19  4388.6 1732.29  4455.5 1731.70  4460.6 1732.49  4470.1 1732.53
  4480.3 1731.82  4602.3 1730.18  4693.7 1730.21  4876.7 1727.18  4886.9 1727.29
  4896.6 1729.72  4901.7 1731.71  4917.4 1728.50  4998.7 1726.99  5013.3 1727.09
  5043.6 1728.73  5072.9 1728.83  5093.8 1730.72  5100.0 1732.81  5108.5 1733.34
  5114.7 1731.46  5123.2 1730.38  5129.4 1727.93  5171.4 1726.92  5171.7 1726.42
  5175.2 1726.42  5175.4 1726.92  5186.5 1727.53  5286.2 1727.79  5350.5 1728.92
#Mann=4,-1,0
  4306.8   0.075       0  4388.6    0.05       0  5171.4    0.03       0
  5175.4    0.05       0
Bank Sta=5171.4,5175.4
Exp/Cntr=0.3,0.1

Chan Stop Cuts=-1