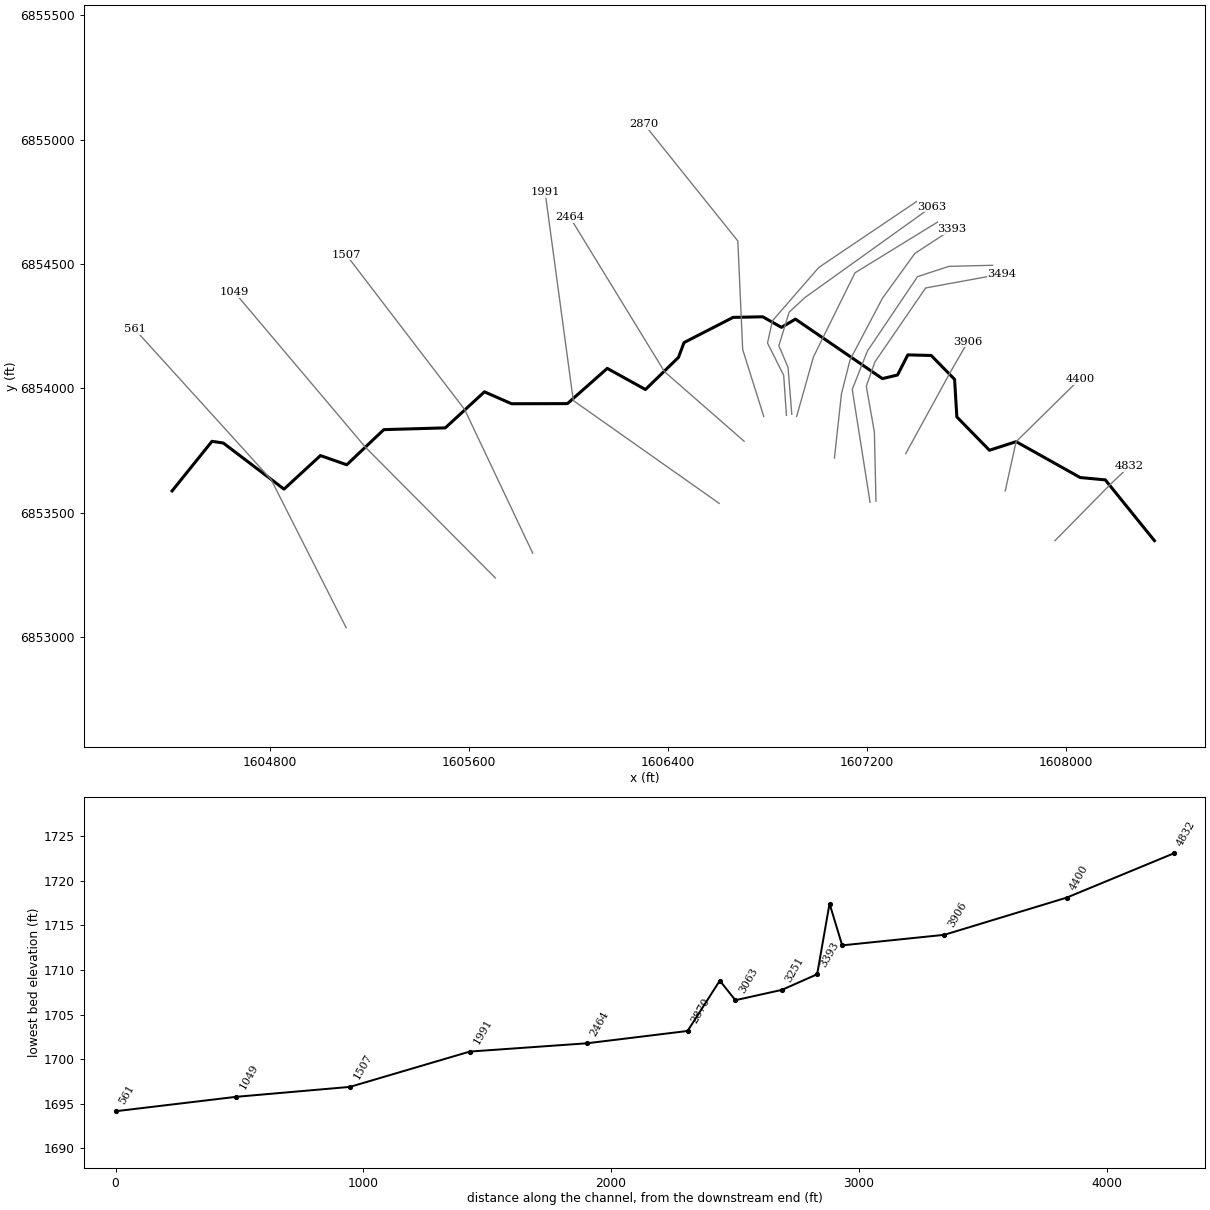
--- Elm 02 28.prj (project) ---

Proj Title=Elm 02 28 Base Level Engineering
Current Plan=p01
Default Exp/Contr=0.3,0.1
English Units
Geom File=g01
Flow File=f01
Plan File=p01
BEGIN DESCRIPTION:
Elm 02 28
END DESCRIPTION:

--- Elm 02 28.p01 (plan) ---

Plan Title=Multiple Run
Short Identifier=Multiple
Geom File=g01
Flow File=f01
Subcritical Flow
K Sum by GR= 0
Std Step Tol= 0.01
Critical Tol= 0.01
Num of Std Step Trials= 20
Max Error Tol= 0.3
Flow Tol Ratio= 0.001
Split Flow NTrial= 30
Split Flow Tol= 0.02
Split Flow Ratio= 0.02
Log Output Level= 0
Friction Slope Method= 1
Unsteady Friction Slope Method= 2
Unsteady Bridges Friction Slope Method= 1
Parabolic Critical Depth
Global Vel Dist=  1 , 1 , 1
Global Log Level= 0
CheckData=True
Encroach Param= -1, 0, 0, 0
BEGIN DESCRIPTION:
Multiple Run
END DESCRIPTION:

--- Elm 02 28.f01 (steady flow) ---

Flow Title=Multiple
Number of Profiles=7
Profile Names=10-year,25-year,50-year,1pct_min,100-year,1pct_plu,500-year
River Rch & RM= Elm 02 28,Reach-1,4832
     166     225     273     206     329     453     485
Boundary for River Rch & Prof#=Elm 02 28,Reach-1,1
Up Type=0
Dn Type=3
Dn Slope=0.001
Boundary for River Rch & Prof#=Elm 02 28,Reach-1,2
Up Type=0
Dn Type=3
Dn Slope=0.001
Boundary for River Rch & Prof#=Elm 02 28,Reach-1,3
Up Type=0
Dn Type=3
Dn Slope=0.001
Boundary for River Rch & Prof#=Elm 02 28,Reach-1,4
Up Type=0
Dn Type=3
Dn Slope=0.001
Boundary for River Rch & Prof#=Elm 02 28,Reach-1,5
Up Type=0
Dn Type=3
Dn Slope=0.001
Boundary for River Rch & Prof#=Elm 02 28,Reach-1,6
Up Type=0
Dn Type=3
Dn Slope=0.001
Boundary for River Rch & Prof#=Elm 02 28,Reach-1,7
Up Type=0
Dn Type=3
Dn Slope=0.001

--- Elm 02 28.g01 (geometry) ---

Geom Title=Existing Conditions

River Reach=Elm 02 28,Reach-1
Reach XY= 30
      1608355.00      6853388.00      1608157.44      6853632.48
      1608056.59      6853641.83      1607798.87      6853786.16
      1607691.62      6853751.54      1607560.47      6853885.55
      1607551.46      6854036.54      1607457.38      6854132.63
      1607363.35      6854135.00      1607322.01      6854054.14
      1607261.09      6854039.57      1606911.66      6854278.69
      1606855.10      6854245.81      1606780.11      6854288.14
      1606660.93      6854285.77      1606463.48      6854184.49
      1606441.27      6854125.02      1606308.41      6853995.77
      1606154.91      6854080.71      1605994.57      6853939.05
      1605770.21      6853938.54      1605661.03      6853986.38
      1605503.54      6853841.54      1605256.46      6853834.46
      1605107.29      6853693.12      1605001.59      6853730.18
      1604855.09      6853595.29      1604611.03      6853780.55
      1604565.49      6853787.52      1604405.00      6853588.00

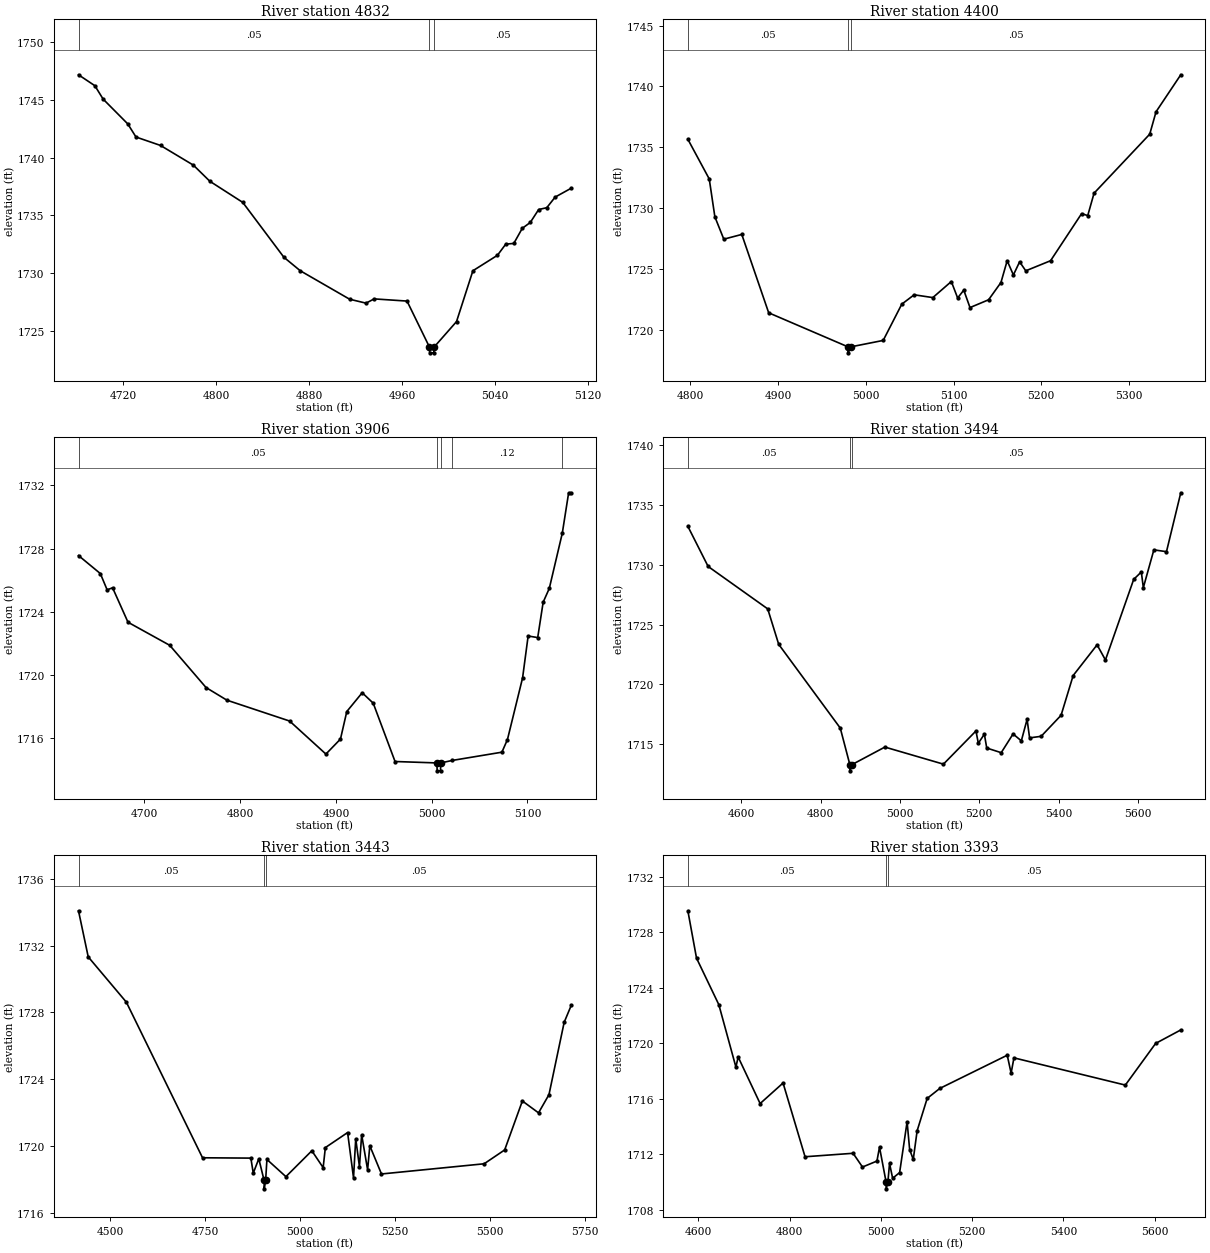
Type RM Length L Ch R = 1,4832,432,432,432
BEGIN DESCRIPTION:
Elm 02 28 4832.071
END DESCRIPTION:
XS GIS Cut Line= 3
      1607955.01      6853388.01      1608178.57      6853615.14
      1608255.01      6853688.01
#Sta/Elev= 30
  4681.3 1747.19  4695.4 1746.24  4702.5 1745.08  4723.7 1742.93  4730.8 1741.79
  4751.9 1741.06  4780.2 1739.35  4794.4 1737.95  4822.7 1736.12  4858.1 1731.36
  4872.2 1730.19  4914.7 1727.72  4928.8 1727.38  4935.8 1727.75  4964.1 1727.56
  4983.4 1723.57  4983.6 1723.07  4987.1 1723.07  4987.4 1723.57  5006.7 1725.78
  5020.8 1730.19  5041.9 1731.53  5049.1 1732.50  5056.0 1732.56  5063.3 1733.87
  5070.2 1734.38  5077.4 1735.50  5084.4 1735.66  5091.6 1736.58  5105.6 1737.36
#Mann=3,-1,0
  4681.3    0.05       0  4983.4    0.05       0  4987.4    0.05       0
Bank Sta=4983.4,4987.4
Exp/Cntr=0.3,0.1

Type RM Length L Ch R = 1,4400,494,494,494
BEGIN DESCRIPTION:
Elm 02 28 4399.843
END DESCRIPTION:
XS GIS Cut Line= 3
      1607754.99      6853587.96      1607798.87      6853786.16
      1608055.00      6854038.00
#Sta/Elev= 30
  4797.0 1735.66  4821.4 1732.40  4827.8 1729.29  4838.0 1727.45  4858.5 1727.84
  4889.2 1721.40  4979.4 1718.61  4979.6 1718.11  4983.4 1718.61  5019.8 1719.13
  5041.0 1722.11  5055.1 1722.88  5076.4 1722.65  5097.5 1723.97  5104.7 1722.62
  5111.7 1723.26  5118.8 1721.83  5140.0 1722.47  5154.1 1723.89  5161.2 1725.68
  5168.3 1724.51  5175.4 1725.59  5182.4 1724.85  5210.7 1725.68  5246.1 1729.55
  5253.1 1729.39  5260.3 1731.23  5323.8 1736.08  5331.0 1737.92  5359.2 1740.96
#Mann=3,-1,0
  4797.0    0.05       0  4979.4    0.03       0  4983.4    0.05       0
Bank Sta=4979.4,4983.4
Exp/Cntr=0.3,0.1

Type RM Length L Ch R = 1,3906,412,412,412
BEGIN DESCRIPTION:
Elm 02 28 3905.906
END DESCRIPTION:
XS GIS Cut Line= 3
      1607355.00      6853738.01      1607532.16      6854061.59
      1607605.00      6854188.00
#Sta/Elev= 30
  4631.1 1727.56  4653.9 1726.42  4661.0 1725.39  4666.7 1725.52  4682.8 1723.34
  4726.4 1721.88  4764.3 1719.21  4786.1 1718.41  4851.6 1717.09  4889.5 1715.00
  4904.7 1715.95  4911.3 1717.69  4927.4 1718.88  4938.9 1718.22  4961.7 1714.53
  5005.4 1714.44  5005.7 1713.94  5009.2 1713.94  5009.4 1714.44  5021.6 1714.60
  5073.3 1715.12  5079.1 1715.92  5094.9 1719.82  5100.7 1722.47  5110.7 1722.37
  5116.4 1724.61  5122.8 1725.48  5136.4 1728.98  5143.0 1731.53  5145.9 1731.53
#Mann=5,-1,0
  4631.1    0.05       0  5005.4    0.03       0  5009.4    0.05       0
  5021.6    0.12       0  5136.4    0.05       0
Bank Sta=5005.4,5009.4
Exp/Cntr=0.3,0.1

Type RM Length L Ch R = 1,3494,51,51,51
BEGIN DESCRIPTION:
Mapping XS ae8b9ebd
END DESCRIPTION:
XS GIS Cut Line= 6
      1607235.43      6853546.88      1607228.92      6853824.62
      1607196.37      6854009.09      1607231.09      6854106.74
      1607435.08      6854404.05      1607741.66      6854460.19
#Sta/Elev= 30
  4465.7 1733.23  4516.8 1729.87  4666.9 1726.32  4694.6 1723.35  4849.7 1716.34
  4874.0 1713.26  4874.3 1712.76  4878.0 1713.26  4962.1 1714.75  5109.6 1713.32
  5191.6 1716.10  5197.5 1715.07  5212.8 1715.83  5218.7 1714.67  5255.2 1714.28
  5285.1 1715.85  5305.9 1715.27  5320.4 1717.07  5326.7 1715.52  5355.8 1715.65
  5406.0 1717.41  5436.5 1720.74  5496.8 1723.31  5517.8 1722.04  5589.0 1728.79
  5608.2 1729.41  5613.3 1728.10  5639.8 1731.26  5671.6 1731.11  5707.6 1736.04
#Mann=3,-1,0
  4465.7    0.05       0  4874.0    0.05       0  4878.0    0.05       0
Bank Sta=4874,4878
Exp/Cntr=0.3,0.1

Type RM Length L Ch R = 1,3443,50,50,50
BEGIN DESCRIPTION:
Mapping XS b1277693
END DESCRIPTION:
XS GIS Cut Line= 6
      1607211.56      6853542.47      1607139.94      6853996.07
      1607200.71      6854150.15      1607402.53      6854449.62
      1607528.40      6854490.86      1607704.13      6854495.20
#Sta/Elev= 30
  4416.1 1734.09  4441.7 1731.33  4542.1 1728.62  4742.8 1719.30  4870.1 1719.28
  4876.4 1718.38  4891.0 1719.24  4905.0 1717.94  4905.3 1717.44  4909.0 1717.94
  4912.4 1719.20  4962.4 1718.17  5030.7 1719.72  5060.5 1718.71  5066.3 1719.91
  5124.9 1720.81  5140.5 1718.10  5146.3 1720.44  5156.1 1718.77  5161.9 1720.68
  5177.6 1718.58  5183.4 1720.02  5214.1 1718.33  5484.5 1718.94  5538.6 1719.77
  5585.2 1722.70  5627.8 1721.99  5655.3 1723.08  5695.3 1727.41  5714.4 1728.45
#Mann=3,-1,0
  4416.1    0.05       0  4905.0    0.05       0  4909.0    0.05       0
Bank Sta=4905,4909
Exp/Cntr=0.3,0.1

Type RM Length L Ch R = 1,3393,142,142,142
BEGIN DESCRIPTION:
Mapping XS 3b520067
END DESCRIPTION:
XS GIS Cut Line= 6
      1607068.33      6853720.50      1607096.54      6853978.70
      1607131.26      6854115.42      1607261.47      6854362.82
      1607391.68      6854542.94      1607540.67      6854640.11
#Sta/Elev= 30
  4576.8 1729.54  4595.8 1726.13  4644.7 1722.78  4682.1 1718.29  4687.1 1719.01
  4735.2 1715.66  4785.5 1717.14  4833.7 1711.83  4939.0 1712.08  4959.6 1711.09
  4991.3 1711.52  4996.9 1712.52  5011.3 1710.02  5011.5 1709.52  5015.3 1710.02
  5018.9 1711.35  5025.7 1710.28  5041.0 1710.69  5057.4 1714.35  5063.0 1712.34
  5070.9 1711.64  5079.4 1713.70  5101.4 1716.03  5129.1 1716.75  5276.9 1719.14
  5285.4 1717.85  5291.6 1718.95  5535.8 1716.99  5602.2 1719.99  5657.3 1720.96
#Mann=3,-1,0
  4576.8    0.05       0  5011.3    0.05       0  5015.3    0.05       0
Bank Sta=5011.3,5015.3
Exp/Cntr=0.3,0.1

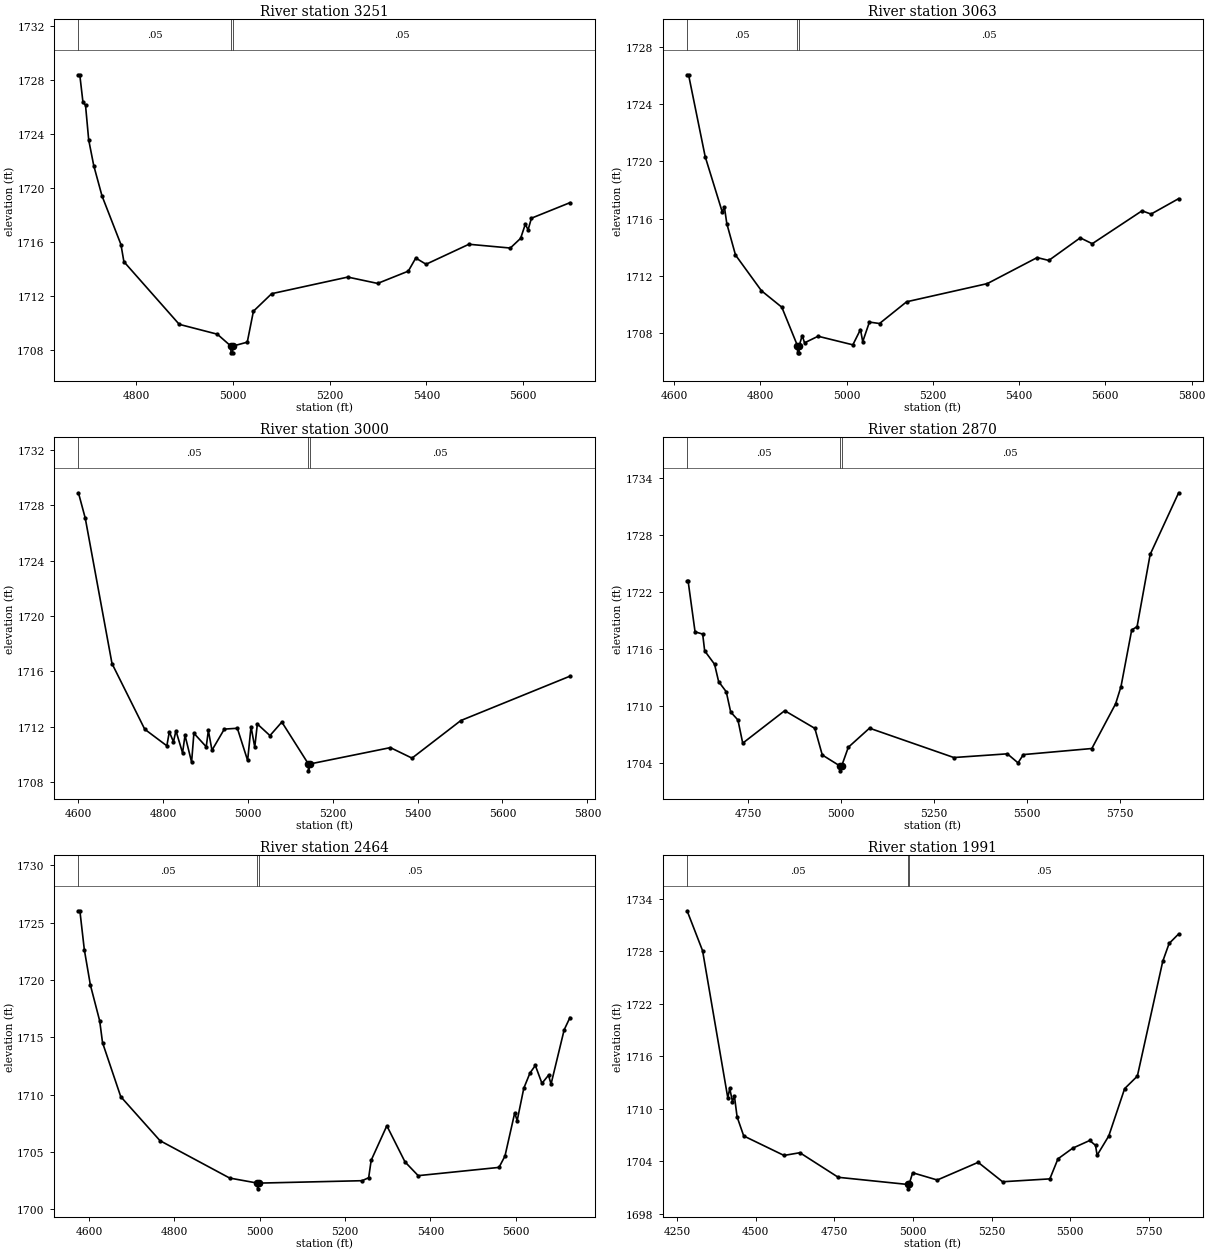
Type RM Length L Ch R = 1,3251,188,188,188
BEGIN DESCRIPTION:
Mapping XS 8cd0c391
END DESCRIPTION:
XS GIS Cut Line= 4
      1606916.43      6853887.58      1606983.69      6854126.27
      1607150.79      6854464.82      1607482.81      6854668.80
#Sta/Elev= 30
  4681.2 1728.36  4684.0 1728.36  4690.6 1726.31  4695.8 1726.12  4702.4 1723.54
  4712.8 1721.64  4729.8 1719.40  4769.0 1715.79  4775.1 1714.52  4889.4 1709.88
  4968.1 1709.15  4996.0 1708.27  4996.3 1707.77  4999.8 1707.77  5000.0 1708.27
  5029.9 1708.56  5042.6 1710.85  5080.3 1712.15  5237.5 1713.38  5299.1 1712.91
  5362.5 1713.82  5377.9 1714.79  5399.2 1714.33  5487.7 1715.81  5573.2 1715.53
  5594.5 1716.25  5604.1 1717.29  5609.9 1716.88  5616.8 1717.74  5696.4 1718.89
#Mann=3,-1,0
  4681.2    0.05       0  4996.0    0.03       0  5000.0    0.05       0
Bank Sta=4996,5000
Exp/Cntr=0.3,0.1

Type RM Length L Ch R = 1,3063,63,63,63
BEGIN DESCRIPTION:
Mapping XS 2b0e5815
END DESCRIPTION:
XS GIS Cut Line= 6
      1606896.89      6853896.20      1606881.70      6854085.04
      1606844.80      6854171.85      1606886.04      6854306.40
      1606948.97      6854364.99      1607460.54      6854731.33
#Sta/Elev= 30
  4630.2 1726.05  4633.6 1726.05  4672.1 1720.33  4711.7 1716.46  4716.7 1716.80
  4722.3 1715.64  4742.4 1713.45  4802.6 1710.95  4849.8 1709.80  4886.1 1707.11
  4886.3 1706.61  4889.8 1706.61  4890.1 1707.11  4897.1 1707.82  4902.5 1707.31
  4933.9 1707.77  5014.5 1707.17  5032.2 1708.24  5037.4 1707.39  5052.9 1708.76
  5076.4 1708.66  5139.2 1710.18  5326.3 1711.45  5441.8 1713.27  5468.8 1713.07
  5541.7 1714.65  5569.6 1714.24  5685.0 1716.54  5705.9 1716.31  5769.9 1717.39
#Mann=3,-1,0
  4630.2    0.05       0  4886.1    0.05       0  4890.1    0.05       0
Bank Sta=4886.1,4890.1
Exp/Cntr=0.3,0.1

Type RM Length L Ch R = 1,3000,130,130,130
BEGIN DESCRIPTION:
Mapping XS 84b83ac2
END DESCRIPTION:
XS GIS Cut Line= 6
      1606875.18      6853891.93      1606864.34      6854052.49
      1606799.23      6854182.70      1606818.76      6854271.67
      1607005.39      6854486.52      1607398.17      6854751.26
#Sta/Elev= 30
  4601.0 1728.92  4617.1 1727.08  4680.1 1716.56  4757.2 1711.81  4809.3 1710.61
  4815.1 1711.62  4824.9 1710.90  4830.7 1711.70  4846.3 1710.10  4852.1 1711.37
  4867.6 1709.43  4873.0 1711.52  4902.1 1710.54  4907.1 1711.72  4915.6 1710.29
  4944.7 1711.82  4975.4 1711.88  4999.6 1709.55  5007.6 1712.00  5016.4 1710.51
  5022.5 1712.19  5052.2 1711.35  5080.2 1712.33  5142.7 1709.30  5142.9 1708.80
  5146.7 1709.30  5335.9 1710.48  5386.9 1709.72  5501.9 1712.44  5759.0 1715.65
#Mann=3,-1,0
  4601.0    0.05       0  5142.7    0.05       0  5146.7    0.05       0
Bank Sta=5142.7,5146.7
Exp/Cntr=0.3,0.1

Type RM Length L Ch R = 1,2870,406,406,406
BEGIN DESCRIPTION:
Mapping XS b42e567a
END DESCRIPTION:
XS GIS Cut Line= 4
      1606784.03      6853887.60      1606699.40      6854156.66
      1606679.87      6854592.85      1606302.58      6855063.38
#Sta/Elev= 30
  4586.1 1723.11  4588.9 1723.11  4607.5 1717.79  4628.0 1717.55  4633.3 1715.79
  4659.9 1714.38  4670.9 1712.55  4691.4 1711.48  4703.3 1709.35  4722.8 1708.51
  4735.7 1706.07  4848.6 1709.49  4929.6 1707.63  4949.6 1704.83  4997.6 1703.66
  4997.9 1703.16  5001.6 1703.66  5019.6 1705.64  5076.6 1707.65  5303.4 1704.56
  5447.2 1704.95  5476.0 1704.00  5490.4 1704.87  5674.5 1705.51  5738.5 1710.22
  5752.9 1712.03  5781.7 1717.99  5796.1 1718.33  5831.3 1725.93  5907.9 1732.42
#Mann=3,-1,0
  4586.1    0.05       0  4997.6    0.03       0  5001.6    0.05       0
Bank Sta=4997.6,5001.6
Exp/Cntr=0.3,0.1

Type RM Length L Ch R = 1,2464,473,473,473
BEGIN DESCRIPTION:
Elm 02 28 2464.443
END DESCRIPTION:
XS GIS Cut Line= 3
      1606705.03      6853787.98      1606384.82      6854067.73
      1606005.01      6854687.98
#Sta/Elev= 30
  4574.8 1726.03  4578.2 1726.03  4588.6 1722.64  4602.8 1719.56  4624.7 1716.42
  4631.3 1714.53  4674.0 1709.82  4766.1 1705.98  4929.4 1702.72  4994.6 1702.28
  4994.8 1701.78  4998.6 1702.28  5239.9 1702.49  5255.3 1702.75  5261.2 1704.27
  5297.9 1707.28  5340.5 1704.13  5371.4 1702.93  5560.9 1703.65  5574.9 1704.64
  5597.7 1708.40  5603.5 1707.73  5619.0 1710.55  5633.5 1711.88  5646.1 1712.54
  5661.6 1710.98  5677.0 1711.69  5682.9 1710.91  5713.7 1715.65  5727.3 1716.72
#Mann=3,-1,0
  4574.8    0.05       0  4994.6    0.03       0  4998.6    0.05       0
Bank Sta=4994.6,4998.6
Exp/Cntr=0.3,0.1

Type RM Length L Ch R = 1,1991,484,484,484
BEGIN DESCRIPTION:
Elm 02 28 1990.519
END DESCRIPTION:
XS GIS Cut Line= 3
      1606605.01      6853537.99      1606018.32      6853951.37
      1605905.00      6854788.03
#Sta/Elev= 30
  4282.3 1732.65  4331.5 1728.08  4411.6 1711.26  4417.8 1712.33  4426.4 1710.83
  4432.6 1711.47  4441.2 1709.08  4462.2 1706.90  4590.2 1704.67  4640.7 1704.98
  4762.6 1702.17  4983.6 1701.35  4983.8 1700.85  4987.6 1701.35  4999.0 1702.69
  5077.3 1701.86  5207.2 1703.88  5284.8 1701.66  5435.0 1701.99  5460.8 1704.28
  5507.6 1705.50  5561.7 1706.38  5580.2 1705.82  5585.2 1704.69  5622.3 1706.90
  5672.7 1712.31  5713.1 1713.74  5793.8 1726.87  5814.0 1728.91  5844.3 1730.00
#Mann=3,-1,0
  4282.3    0.05       0  4983.6    0.03       0  4987.6    0.05       0
Bank Sta=4983.6,4987.6
Exp/Cntr=0.3,0.1

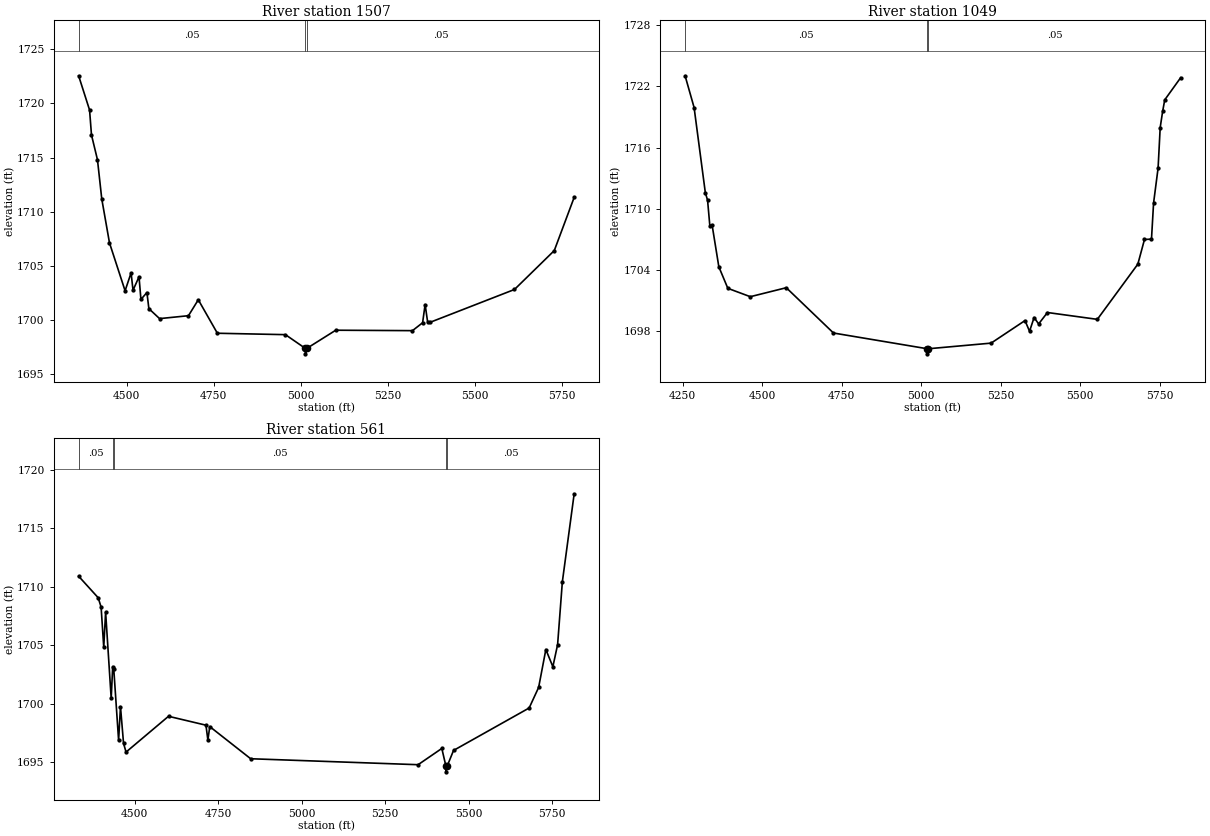
Type RM Length L Ch R = 1,1507,458,458,458
BEGIN DESCRIPTION:
Elm 02 28 1506.724
END DESCRIPTION:
XS GIS Cut Line= 3
      1605855.02      6853337.96      1605581.74      6853914.69
      1605105.02      6854537.98
#Sta/Elev= 30
  4361.8 1722.55  4393.2 1719.39  4398.7 1717.09  4415.9 1714.80  4428.2 1711.19
  4450.4 1707.13  4495.2 1702.71  4512.4 1704.36  4518.0 1702.76  4535.2 1704.00
  4540.7 1701.91  4557.9 1702.55  4563.5 1701.06  4594.2 1700.14  4677.2 1700.41
  4705.4 1701.88  4760.2 1698.79  4955.6 1698.66  5012.9 1697.39  5013.1 1696.89
  5016.9 1697.39  5100.1 1699.07  5320.4 1699.03  5349.5 1699.76  5356.7 1701.44
  5364.0 1699.81  5370.3 1699.79  5613.3 1702.83  5727.6 1706.42  5784.7 1711.33
#Mann=3,-1,0
  4361.8    0.05       0  5012.9    0.03       0  5016.9    0.05       0
Bank Sta=5012.9,5016.9
Exp/Cntr=0.3,0.1

Type RM Length L Ch R = 1,1049,488,488,488
BEGIN DESCRIPTION:
Elm 02 28 1049.12
END DESCRIPTION:
XS GIS Cut Line= 3
      1605705.00      6853238.00      1605181.65      6853764.56
      1604655.01      6854387.99
#Sta/Elev= 30
  4257.6 1723.03  4285.9 1719.92  4321.2 1711.58  4328.3 1710.83  4335.4 1708.33
  4342.4 1708.43  4363.7 1704.31  4392.0 1702.20  4462.7 1701.38  4575.8 1702.26
  4724.3 1697.82  5019.1 1696.28  5019.3 1695.78  5023.1 1696.28  5220.0 1696.83
  5326.6 1699.04  5340.9 1697.99  5355.2 1699.34  5369.5 1698.71  5397.2 1699.83
  5554.1 1699.16  5681.5 1704.57  5702.4 1706.99  5724.4 1707.02  5731.0 1710.56
  5745.2 1713.99  5751.8 1717.96  5759.5 1719.54  5766.1 1720.67  5816.1 1722.84
#Mann=3,-1,0
  4257.6    0.05       0  5019.1    0.03       0  5023.1    0.05       0
Bank Sta=5019.1,5023.1
Exp/Cntr=0.3,0.1

Type RM Length L Ch R = 1,561,0,0,0
BEGIN DESCRIPTION:
Elm 02 28 561.198
END DESCRIPTION:
XS GIS Cut Line= 3
      1605105.01      6853037.97      1604803.35      6853633.53
      1604255.02      6854237.98
#Sta/Elev= 30
  4332.4 1710.89  4390.9 1709.05  4399.7 1708.25  4407.6 1704.81  4413.2 1707.82
  4429.9 1700.44  4434.4 1703.16  4437.6 1702.95  4452.1 1696.85  4457.7 1699.74
  4466.9 1696.59  4474.4 1695.85  4601.5 1698.91  4713.6 1698.15  4719.4 1696.88
  4725.0 1698.03  4847.5 1695.28  5348.8 1694.77  5419.8 1696.16  5432.0 1694.66
  5432.2 1694.16  5436.0 1694.66  5454.9 1695.99  5681.3 1699.62  5709.7 1701.38
  5731.3 1704.62  5752.3 1703.15  5766.5 1705.04  5780.7 1710.41  5816.1 1717.94
#Mann=5,-1,0
  4332.4    0.05       0  4434.4   0.075       0  4437.6    0.05       0
  5432.0    0.03       0  5436.0    0.05       0
Bank Sta=5432,5436
Exp/Cntr=0.3,0.1

Chan Stop Cuts=-1