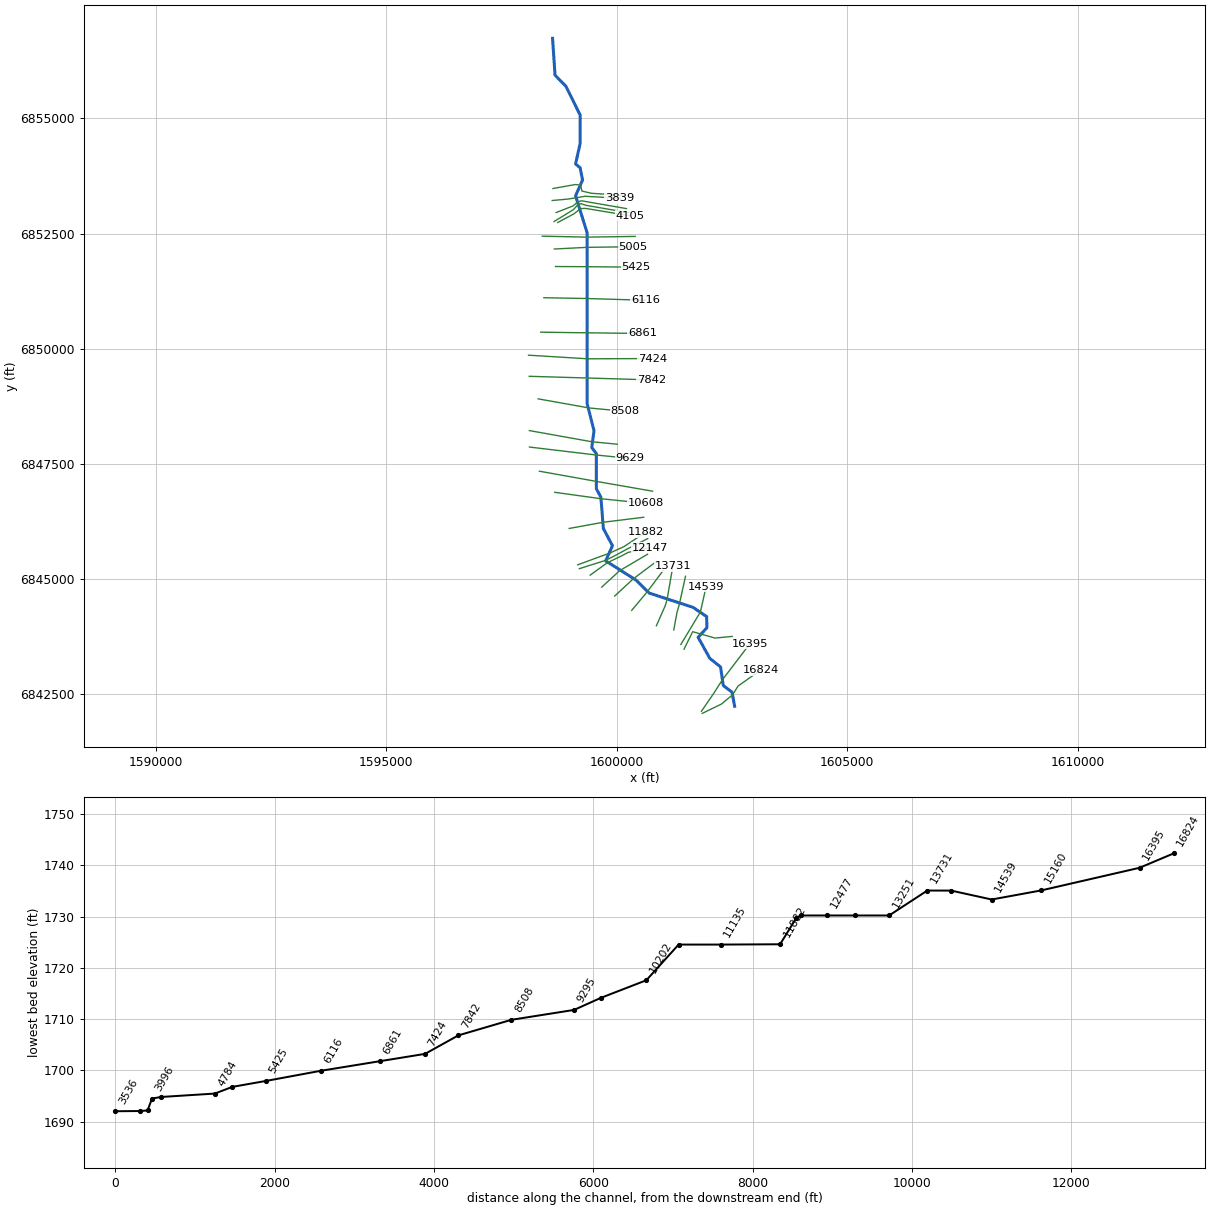
--- Elm 02 30.prj (project) ---

Proj Title=Elm 02 30 Base Level Engineering
Current Plan=p01
Default Exp/Contr=0.3,0.1
English Units
Geom File=g01
Flow File=f01
Plan File=p01
BEGIN DESCRIPTION:
Elm 02 30
END DESCRIPTION:

--- Elm 02 30.p01 (plan) ---

Plan Title=Multiple Run
Short Identifier=Multiple
Geom File=g01
Flow File=f01
Subcritical Flow
K Sum by GR= 0
Std Step Tol= 0.01
Critical Tol= 0.01
Num of Std Step Trials= 20
Max Error Tol= 0.3
Flow Tol Ratio= 0.001
Split Flow NTrial= 30
Split Flow Tol= 0.02
Split Flow Ratio= 0.02
Log Output Level= 0
Friction Slope Method= 1
Unsteady Friction Slope Method= 2
Unsteady Bridges Friction Slope Method= 1
Parabolic Critical Depth
Global Vel Dist=  1 , 1 , 1
Global Log Level= 0
CheckData=True
Encroach Param= -1, 0, 0, 0
BEGIN DESCRIPTION:
Multiple Run
END DESCRIPTION:

--- Elm 02 30.f01 (steady flow) ---

Flow Title=Multiple
Number of Profiles=7
Profile Names=10-year,25-year,50-year,1pct_min,100-year,1pct_plu,500-year
River Rch & RM= Elm 02 30,Reach-1,16824
     249     340     414     312     500     688     740
River Rch & RM= Elm 02 30,Reach-1,10608
     347     484     597     456     731    1010    1110
River Rch & RM= Elm 02 30,Reach-1,5425
     425     598     742     570     913    1260    1400
Boundary for River Rch & Prof#=Elm 02 30,Reach-1,1
Up Type=0
Dn Type=3
Dn Slope=0.001
Boundary for River Rch & Prof#=Elm 02 30,Reach-1,2
Up Type=0
Dn Type=3
Dn Slope=0.001
Boundary for River Rch & Prof#=Elm 02 30,Reach-1,3
Up Type=0
Dn Type=3
Dn Slope=0.001
Boundary for River Rch & Prof#=Elm 02 30,Reach-1,4
Up Type=0
Dn Type=3
Dn Slope=0.001
Boundary for River Rch & Prof#=Elm 02 30,Reach-1,5
Up Type=0
Dn Type=3
Dn Slope=0.001
Boundary for River Rch & Prof#=Elm 02 30,Reach-1,6
Up Type=0
Dn Type=3
Dn Slope=0.001
Boundary for River Rch & Prof#=Elm 02 30,Reach-1,7
Up Type=0
Dn Type=3
Dn Slope=0.001

--- Elm 02 30.g01 (geometry) ---

Geom Title=Existing Conditions

River Reach=Elm 02 30,Reach-1
Reach XY= 30
      1602555.00      6842238.00      1602499.27      6842540.55
      1602308.61      6842689.48      1602249.64      6843090.70
      1602015.76      6843278.32      1601762.83      6843734.78
      1601951.26      6843939.52      1601949.82      6844182.56
      1601653.42      6844384.18      1600702.70      6844693.83
      1600414.68      6844977.22      1599756.69      6845393.63
      1599904.63      6845722.73      1599706.22      6846098.50
      1599653.80      6846777.50      1599555.20      6846956.26
      1599554.46      6847724.14      1599455.25      6847853.22
      1599504.50      6848219.32      1599355.07      6848808.03
      1599355.11      6852515.33      1599104.57      6853319.67
      1599255.22      6853660.66      1599203.02      6853926.80
      1599104.49      6854010.67      1599204.96      6854460.77
      1599204.80      6855069.74      1598896.86      6855694.06
      1598658.54      6855939.47      1598605.00      6856738.00

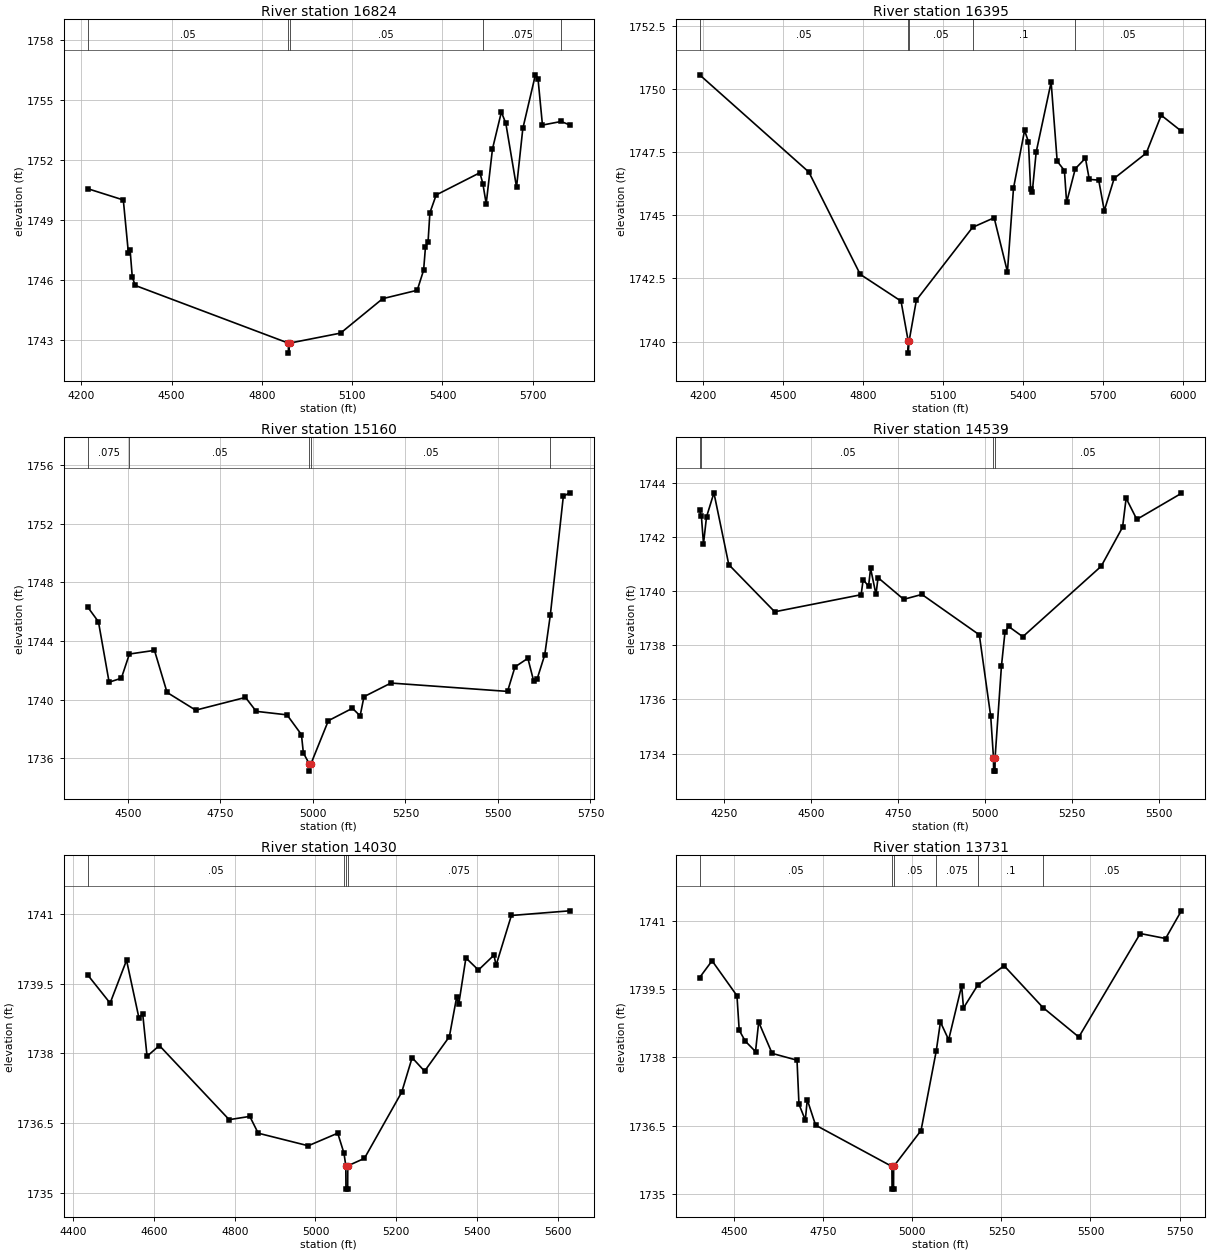
Type RM Length L Ch R = 1,16824,429,429,429
BEGIN DESCRIPTION:
Elm 02 30 16891.524
END DESCRIPTION:
XS GIS Cut Line= 5
      1601852.22      6842082.61      1602264.58      6842282.28
      1602511.15      6842485.85      1602629.16      6842675.08
      1603117.48      6843022.32
#Sta/Elev= 30
  4222.1 1750.56  4339.8 1750.00  4356.8 1747.34  4362.4 1747.49  4369.6 1746.15
  4379.4 1745.73  4888.1 1742.85  4888.4 1742.35  4892.2 1742.85  5061.5 1743.35
  5201.3 1745.07  5316.1 1745.49  5337.3 1746.49  5343.5 1747.65  5352.1 1747.91
  5358.2 1749.36  5379.1 1750.25  5524.3 1751.36  5534.2 1750.81  5545.2 1749.81
  5566.1 1752.55  5595.6 1754.39  5610.4 1753.83  5646.0 1750.64  5666.9 1753.57
  5708.7 1756.25  5717.3 1756.06  5732.1 1753.74  5794.1 1753.92  5822.2 1753.75
#Mann=5,-1,0
  4222.1    0.05       0  4888.1    0.03       0  4892.2    0.05       0
  5534.2   0.075       0  5794.1    0.05       0
Bank Sta=4888.1,4892.2
Exp/Cntr=0.3,0.1

Type RM Length L Ch R = 1,16395,1235,1235,1235
BEGIN DESCRIPTION:
Elm 02 30 16394.93
END DESCRIPTION:
XS GIS Cut Line= 4
      1601834.89      6842128.93      1602106.16      6842523.89
      1602288.45      6842810.35      1602889.58      6843598.10
#Sta/Elev= 30
  4185.8 1750.56  4596.1 1746.71  4789.1 1742.66  4942.4 1741.60  4969.0 1740.04
  4969.3 1739.54  4973.1 1740.04  5000.1 1741.64  5211.2 1744.52  5292.2 1744.90
  5342.1 1742.76  5364.9 1746.07  5406.5 1748.36  5421.0 1747.91  5429.2 1746.04
  5435.6 1745.94  5450.1 1747.50  5506.3 1750.27  5529.0 1747.14  5556.2 1746.77
  5564.4 1745.51  5597.0 1746.84  5635.1 1747.26  5649.6 1746.42  5685.0 1746.39
  5706.0 1745.18  5743.1 1746.46  5863.7 1747.46  5919.9 1748.96  5995.4 1748.33
#Mann=5,-1,0
  4185.8    0.05       0  4969.0    0.05       0  4973.1    0.05       0
  5211.2     0.1       0  5597.0    0.05       0
Bank Sta=4969,4973.1
Exp/Cntr=0.3,0.1

Type RM Length L Ch R = 1,15160,621,621,621
BEGIN DESCRIPTION:
Mapping XS 7d9cf709
END DESCRIPTION:
XS GIS Cut Line= 4
      1601457.80      6843476.48      1601644.43      6843856.24
      1602128.37      6843717.35      1602501.85      6843754.05
#Sta/Elev= 30
  4391.6 1746.30  4420.2 1745.31  4449.0 1741.19  4482.1 1741.46  4503.8 1743.11
  4571.6 1743.36  4605.6 1740.49  4683.0 1739.28  4817.6 1740.15  4846.5 1739.20
  4929.8 1738.96  4968.8 1737.61  4974.0 1736.36  4989.9 1735.62  4990.2 1735.12
  4994.5 1735.62  5041.5 1738.56  5106.6 1739.41  5127.4 1738.89  5137.8 1740.20
  5210.7 1741.13  5525.8 1740.56  5545.9 1742.23  5580.8 1742.82  5596.2 1741.29
  5606.2 1741.44  5626.3 1743.05  5641.4 1745.76  5676.6 1753.87  5693.5 1754.11
#Mann=5,-1,0
  4391.6   0.075       0  4503.8    0.05       0  4989.9    0.03       0
  4994.5    0.05       0  5641.4   0.075       0
Bank Sta=4989.9,4994.5
Exp/Cntr=0.3,0.1

Type RM Length L Ch R = 1,14539,509,509,509
BEGIN DESCRIPTION:
Elm 02 30 14539.67
END DESCRIPTION:
XS GIS Cut Line= 3
      1601388.37      6843578.49      1601812.66      6844284.45
      1601935.91      6844833.02
#Sta/Elev= 30
  4179.2 1742.97  4184.3 1742.75  4190.3 1741.74  4199.0 1742.73  4220.3 1743.62
  4263.1 1740.97  4395.2 1739.23  4643.9 1739.86  4649.7 1740.42  4665.2 1740.17
  4671.1 1740.83  4686.6 1739.87  4692.5 1740.49  4766.3 1739.69  4818.7 1739.87
  4983.9 1738.38  5016.7 1735.37  5024.6 1733.85  5025.0 1733.35  5029.0 1733.35
  5029.3 1733.85  5047.5 1737.22  5057.7 1738.48  5068.0 1738.69  5109.0 1738.31
  5334.5 1740.91  5396.0 1742.35  5406.3 1743.42  5437.0 1742.64  5565.1 1743.60
#Mann=4,-1,0
  4179.2   0.075       0  4184.3    0.05       0  5024.6    0.03       0
  5029.3    0.05       0
Bank Sta=5024.6,5029.3
Exp/Cntr=0.3,0.1

Type RM Length L Ch R = 1,14030,299,299,299
BEGIN DESCRIPTION:
Elm 02 30 14029.68
END DESCRIPTION:
XS GIS Cut Line= 4
      1601234.53      6843893.83      1601305.71      6844279.24
      1601354.32      6844445.91      1601489.74      6845058.78
#Sta/Elev= 30
  4436.3 1739.68  4491.4 1739.08  4532.1 1740.00  4562.6 1738.77  4572.1 1738.85
  4582.9 1737.94  4613.4 1738.17  4786.3 1736.58  4837.4 1736.65  4858.2 1736.29
  4982.2 1736.02  5055.2 1736.29  5070.7 1735.86  5075.2 1735.59  5075.6 1735.09
  5079.8 1735.09  5080.1 1735.59  5121.3 1735.75  5213.7 1737.17  5239.5 1737.91
  5270.3 1737.62  5331.7 1738.36  5349.8 1739.21  5355.0 1739.06  5372.7 1740.05
  5403.7 1739.79  5442.3 1740.11  5447.4 1739.89  5485.3 1740.96  5629.5 1741.06
#Mann=4,-1,0
  4436.3    0.05       0  5070.7   0.075       0  5075.2    0.03       0
  5080.1   0.075       0
Bank Sta=5075.2,5080.1
Exp/Cntr=0.3,0.1

Type RM Length L Ch R = 1,13731,480,480,480
BEGIN DESCRIPTION:
Elm 02 30 13731.24
END DESCRIPTION:
XS GIS Cut Line= 4
      1600857.97      6843986.36      1601048.94      6844418.65
      1601087.14      6844543.65      1601215.62      6845281.55
#Sta/Elev= 30
  4402.8 1739.76  4437.7 1740.13  4507.6 1739.36  4513.9 1738.60  4530.9 1738.36
  4559.7 1738.13  4568.6 1738.78  4606.3 1738.09  4676.2 1737.94  4681.7 1736.97
  4699.5 1736.62  4705.0 1737.07  4728.3 1736.51  4942.6 1735.60  4943.0 1735.10
  4947.2 1735.10  4947.5 1735.60  5024.3 1736.39  5067.0 1738.14  5078.8 1738.78
  5101.9 1738.39  5138.4 1739.58  5143.5 1739.09  5183.3 1739.59  5257.6 1740.02
  5366.6 1739.10  5467.3 1738.45  5639.8 1740.73  5710.9 1740.62  5755.1 1741.23
#Mann=6,-1,0
  4402.8    0.05       0  4942.6    0.03       0  4947.5    0.05       0
  5067.0   0.075       0  5183.3     0.1       0  5366.6    0.05       0
Bank Sta=4942.6,4947.5
Exp/Cntr=0.3,0.1

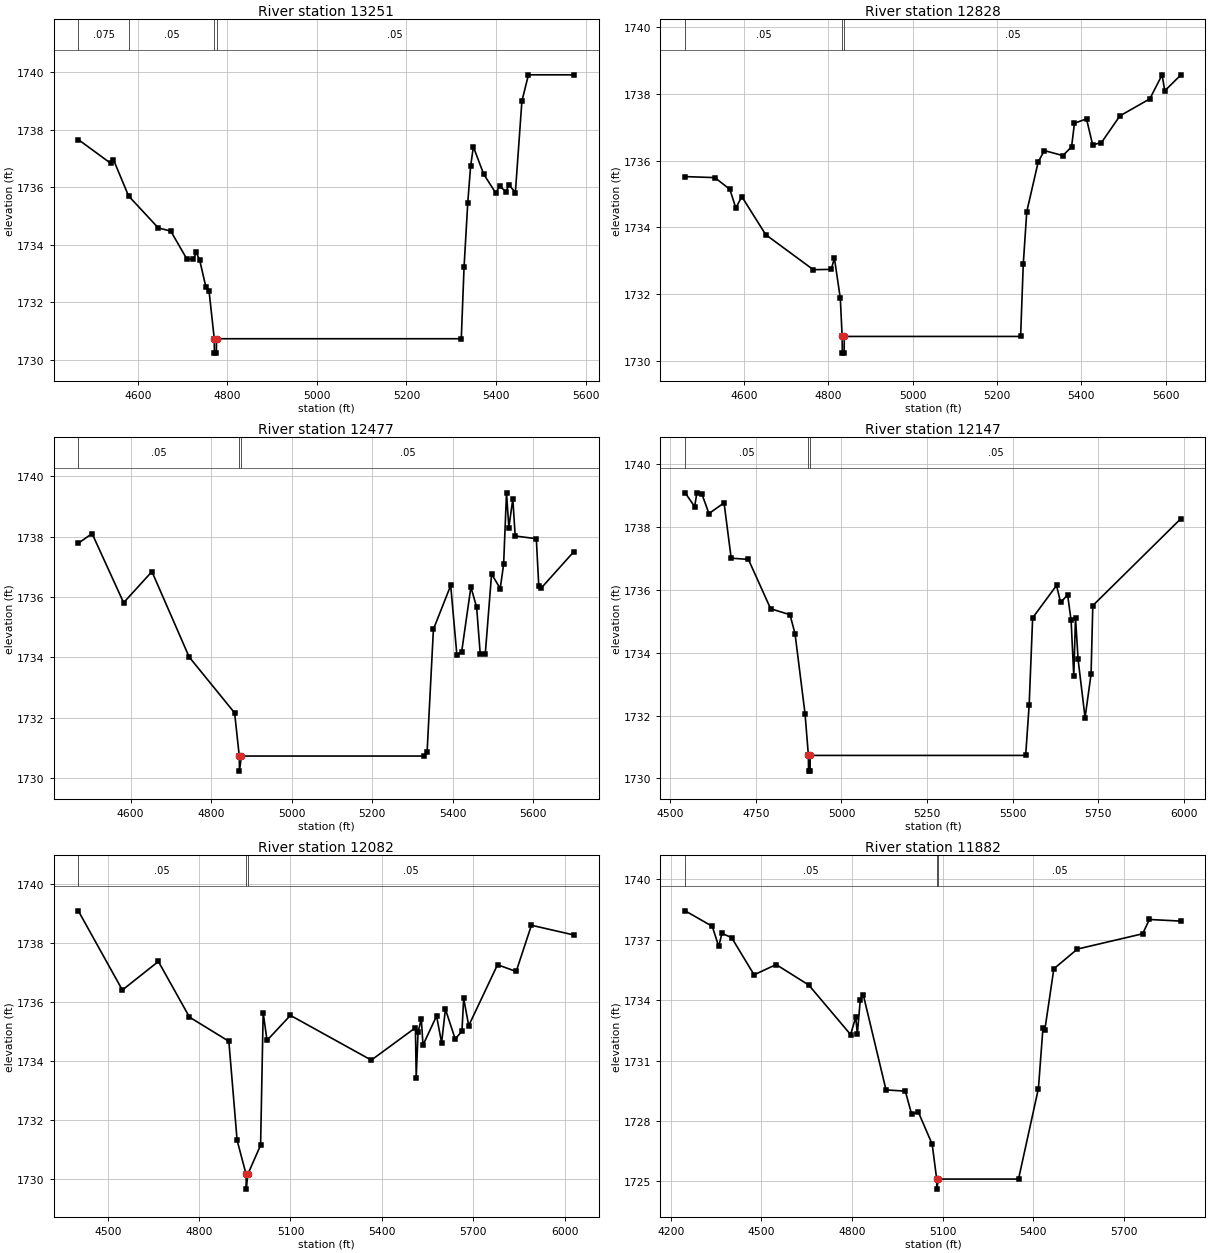
Type RM Length L Ch R = 1,13251,423,423,423
BEGIN DESCRIPTION:
Elm 02 30 13250.93
END DESCRIPTION:
XS GIS Cut Line= 3
      1600322.38      6844319.55      1600665.26      6844729.71
      1601008.12      6845187.57
#Sta/Elev= 30
  4467.2 1737.65  4539.2 1736.83  4545.7 1736.95  4579.5 1735.69  4645.9 1734.58
  4673.7 1734.47  4709.6 1733.50  4723.9 1733.49  4730.5 1733.73  4738.3 1733.46
  4751.9 1732.54  4759.1 1732.40  4770.8 1730.73  4771.2 1730.23  4775.5 1730.23
  4775.9 1730.73  5322.5 1730.73  5328.7 1733.22  5337.0 1735.46  5343.3 1736.72
  5349.5 1737.40  5372.5 1736.45  5399.6 1735.79  5407.9 1736.03  5422.5 1735.84
  5428.7 1736.08  5443.3 1735.81  5457.9 1738.99  5472.5 1739.90  5573.8 1739.90
#Mann=4,-1,0
  4467.2   0.075       0  4579.5    0.05       0  4770.8    0.03       0
  4775.9    0.05       0
Bank Sta=4770.8,4775.9
Exp/Cntr=0.3,0.1

Type RM Length L Ch R = 1,12828,351,351,351
BEGIN DESCRIPTION:
Elm 02 30 12828.46
END DESCRIPTION:
XS GIS Cut Line= 3
      1599953.47      6844629.89      1600350.59      6844998.80
      1600856.22      6845378.57
#Sta/Elev= 30
  4461.0 1735.52  4531.3 1735.49  4566.9 1735.14  4581.1 1734.58  4595.3 1734.92
  4652.0 1733.78  4764.8 1732.73  4807.3 1732.74  4814.7 1733.08  4828.8 1731.87
  4833.1 1730.73  4833.5 1730.23  4837.9 1730.23  4838.2 1730.73  5256.1 1730.73
  5262.4 1732.90  5270.7 1734.47  5297.8 1735.96  5312.4 1736.30  5356.1 1736.15
  5376.9 1736.41  5383.7 1737.12  5412.3 1737.25  5426.9 1736.47  5447.7 1736.54
  5491.5 1737.34  5562.3 1737.85  5591.5 1738.57  5597.7 1738.09  5635.4 1738.56
#Mann=3,-1,0
  4461.0    0.05       0  4833.1    0.03       0  4838.2    0.05       0
Bank Sta=4833.1,4838.2
Exp/Cntr=0.3,0.1

Type RM Length L Ch R = 1,12477,330,330,330
BEGIN DESCRIPTION:
Elm 02 30 12477.24
END DESCRIPTION:
XS GIS Cut Line= 3
      1599671.36      6844823.04      1600064.13      6845183.27
      1600665.24      6845536.98
#Sta/Elev= 30
  4470.3 1737.78  4504.5 1738.10  4582.8 1735.81  4653.1 1736.84  4745.6 1734.01
  4858.4 1732.16  4870.0 1730.73  4870.4 1730.23  4875.3 1730.73  5329.1 1730.73
  5336.4 1730.86  5352.1 1734.93  5395.0 1736.38  5410.4 1734.07  5422.3 1734.19
  5445.2 1736.33  5459.4 1735.66  5468.4 1734.10  5480.9 1734.12  5496.5 1736.76
  5518.0 1736.28  5526.4 1737.08  5533.6 1739.45  5539.4 1738.30  5549.3 1739.25
  5555.1 1738.02  5607.6 1737.93  5613.7 1736.37  5619.5 1736.29  5700.7 1737.50
#Mann=3,-1,0
  4470.3    0.05       0  4870.0    0.03       0  4875.3    0.05       0
Bank Sta=4870,4875.3
Exp/Cntr=0.3,0.1

Type RM Length L Ch R = 1,12147,65,65,65
BEGIN DESCRIPTION:
Elm 02 30 12146.89
END DESCRIPTION:
XS GIS Cut Line= 5
      1599421.51      6845083.82      1599791.27      6845352.03
      1600122.00      6845510.88      1600247.00      6845578.59
      1600718.40      6845674.96
#Sta/Elev= 30
  4543.5 1739.09  4571.3 1738.65  4577.4 1739.07  4592.1 1739.06  4613.0 1738.43
  4657.1 1738.77  4677.9 1737.01  4728.2 1736.97  4793.1 1735.40  4849.6 1735.21
  4864.3 1734.61  4893.6 1732.06  4903.4 1730.73  4903.8 1730.23  4908.3 1730.23
  4908.7 1730.73  5537.9 1730.73  5548.1 1732.33  5558.3 1735.11  5628.0 1736.14
  5640.0 1735.60  5660.4 1735.84  5670.6 1735.03  5678.4 1733.26  5683.5 1735.12
  5691.0 1733.79  5711.4 1731.93  5728.9 1733.32  5734.0 1735.50  5990.5 1738.26
#Mann=3,-1,0
  4543.5    0.05       0  4903.4    0.03       0  4908.7    0.05       0
Bank Sta=4903.4,4908.7
Exp/Cntr=0.3,0.1

Type RM Length L Ch R = 1,12082,200,200,200
BEGIN DESCRIPTION:
Elm 02 30 12081.52
END DESCRIPTION:
XS GIS Cut Line= 5
      1599187.10      6845224.42      1599754.82      6845404.11
      1599926.69      6845490.05      1600205.34      6845641.09
      1600670.76      6845877.70
#Sta/Elev= 30
  4403.4 1739.10  4548.0 1736.41  4666.2 1737.38  4768.4 1735.49  4897.6 1734.67
  4924.7 1731.31  4954.3 1730.15  4954.7 1729.65  4959.6 1730.15  5001.8 1731.14
  5010.3 1735.64  5022.9 1734.70  5099.7 1735.55  5365.3 1734.03  5510.1 1735.13
  5512.7 1733.44  5518.8 1734.97  5529.4 1735.44  5535.0 1734.54  5579.5 1735.53
  5596.1 1734.62  5608.6 1735.76  5640.6 1734.75  5662.9 1735.01  5668.5 1736.13
  5685.1 1735.20  5779.7 1737.27  5840.9 1737.04  5891.0 1738.61  6030.1 1738.28
#Mann=3,-1,0
  4403.4    0.05       0  4954.3    0.03       0  4959.6    0.05       0
Bank Sta=4954.3,4959.6
Exp/Cntr=0.3,0.1

Type RM Length L Ch R = 1,11882,747,747,747
BEGIN DESCRIPTION:
Elm 02 30 11881.77
END DESCRIPTION:
XS GIS Cut Line= 4
      1599150.69      6845307.77      1599858.98      6845568.18
      1600155.86      6845703.59      1600620.97      6846015.40
#Sta/Elev= 30
  4247.6 1738.44  4337.4 1737.67  4358.7 1736.67  4369.4 1737.32  4401.4 1737.11
  4475.9 1735.26  4548.9 1735.77  4657.1 1734.75  4795.6 1732.29  4812.5 1733.16
  4817.8 1732.32  4827.5 1734.01  4837.6 1734.26  4912.8 1729.54  4976.7 1729.48
  4997.5 1728.34  5019.8 1728.44  5065.7 1726.84  5080.6 1725.11  5081.0 1724.61
  5085.9 1725.11  5351.6 1725.11  5417.5 1729.61  5432.5 1732.61  5438.6 1732.51
  5468.6 1735.56  5546.6 1736.54  5762.7 1737.30  5785.0 1738.01  5888.5 1737.93
#Mann=3,-1,0
  4247.6    0.05       0  5080.6    0.05       0  5085.9    0.05       0
Bank Sta=5080.6,5085.9
Exp/Cntr=0.3,0.1

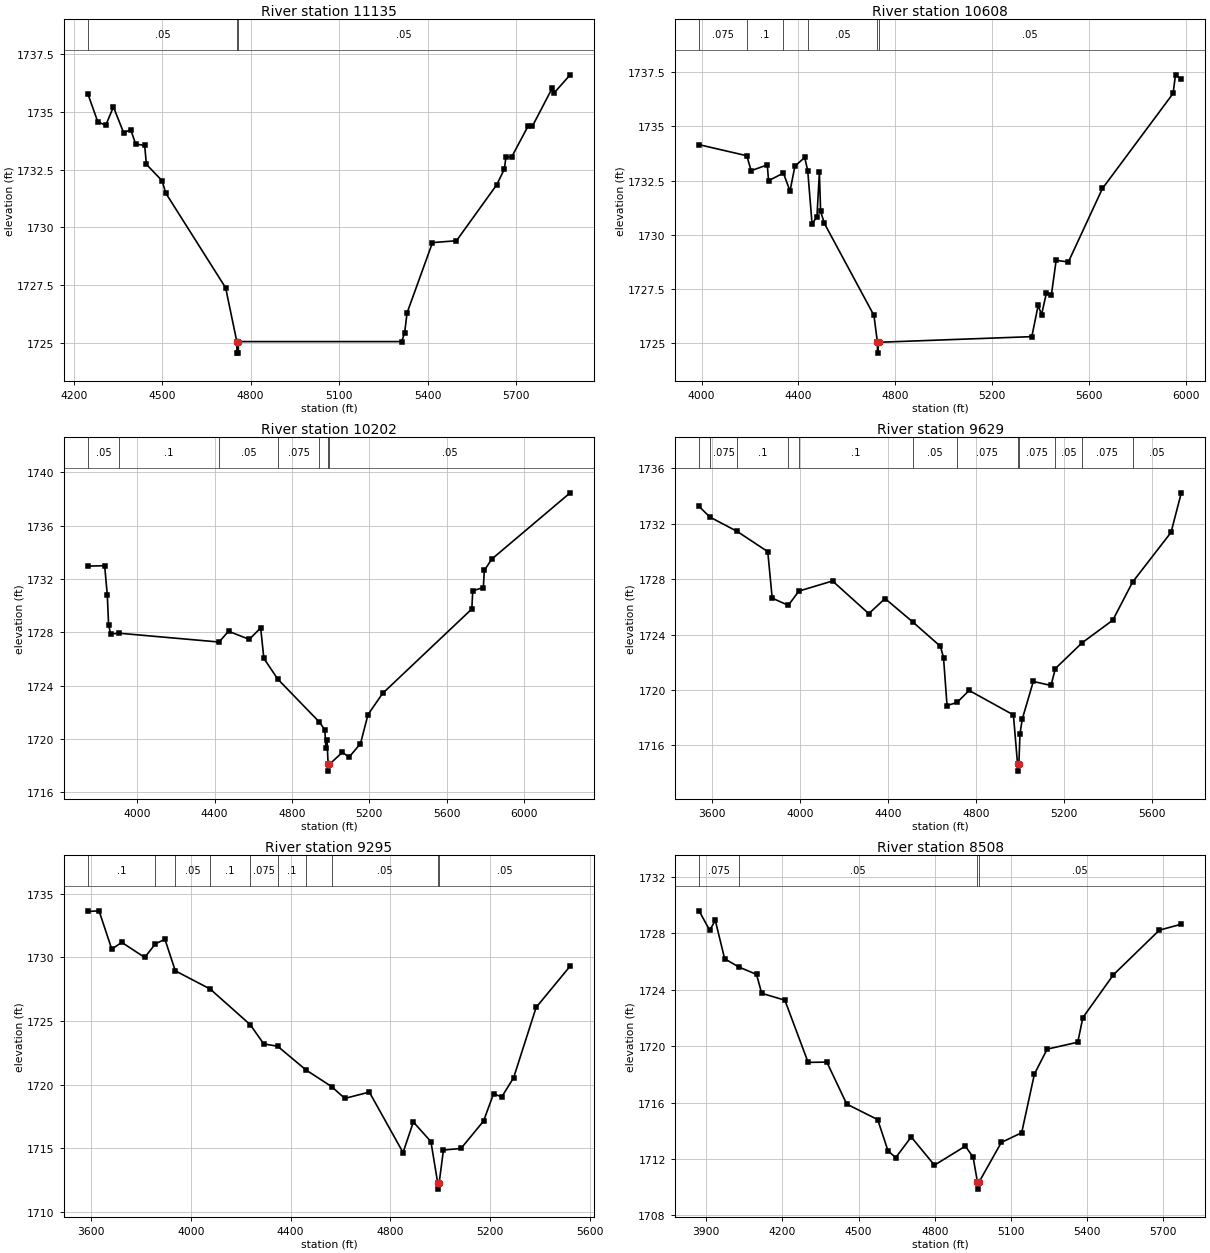
Type RM Length L Ch R = 1,11135,527,527,527
BEGIN DESCRIPTION:
Elm 02 30 11134.87
END DESCRIPTION:
XS GIS Cut Line= 3
      1598965.58      6846097.33      1599708.63      6846232.74
      1600581.86      6846340.16
#Sta/Elev= 30
  4248.1 1735.78  4281.4 1734.58  4308.5 1734.42  4334.7 1735.22  4369.5 1734.09
  4393.1 1734.24  4410.1 1733.61  4440.6 1733.55  4446.4 1732.73  4499.7 1732.02
  4511.8 1731.49  4715.1 1727.38  4753.0 1725.05  4753.4 1724.55  4758.0 1724.55
  4758.4 1725.05  5312.1 1725.05  5322.1 1725.44  5330.1 1726.29  5416.4 1729.34
  5497.7 1729.42  5634.5 1731.85  5660.2 1732.53  5665.2 1733.03  5684.9 1733.05
  5741.4 1734.41  5755.4 1734.39  5822.7 1736.04  5827.7 1735.81  5883.2 1736.61
#Mann=3,-1,0
  4248.1    0.05       0  4753.0    0.03       0  4758.4    0.05       0
Bank Sta=4753,4758.4
Exp/Cntr=0.3,0.1

Type RM Length L Ch R = 1,10608,406,406,406
BEGIN DESCRIPTION:
Elm 02 30 10608.37
END DESCRIPTION:
XS GIS Cut Line= 3
      1598653.06      6846882.05      1599653.08      6846743.16
      1600628.77      6846642.47
#Sta/Elev= 30
  3989.5 1734.16  4186.6 1733.65  4204.6 1732.96  4271.2 1733.23  4276.3 1732.50
  4337.8 1732.85  4365.0 1732.02  4385.2 1733.17  4425.6 1733.57  4438.1 1732.96
  4455.9 1730.52  4476.1 1730.82  4486.2 1732.88  4491.3 1731.09  4506.4 1730.54
  4711.4 1726.29  4725.7 1725.05  4726.1 1724.55  4731.3 1725.05  5363.0 1725.31
  5389.2 1726.75  5403.2 1726.32  5423.3 1727.33  5443.4 1727.21  5463.5 1728.83
  5513.8 1728.75  5654.5 1732.14  5946.0 1736.52  5956.1 1737.38  5980.0 1737.18
#Mann=6,-1,0
  3989.5   0.075       0  4186.6     0.1       0  4337.8   0.075       0
  4438.1    0.05       0  4725.7    0.03       0  4731.3    0.05       0
Bank Sta=4725.7,4731.3
Exp/Cntr=0.3,0.1

Type RM Length L Ch R = 1,10202,573,573,573
BEGIN DESCRIPTION:
Elm 02 30 10202.04
END DESCRIPTION:
XS GIS Cut Line= 3
      1598319.74      6847340.38      1599559.33      6847118.16
      1600774.65      6846906.35
#Sta/Elev= 30
  3745.0 1732.97  3831.6 1733.00  3845.2 1730.81  3851.9 1728.58  3862.1 1727.88
  3907.9 1727.93  4423.1 1727.27  4471.8 1728.08  4579.3 1727.47  4638.1 1728.33
  4654.5 1726.05  4726.3 1724.49  4940.4 1721.28  4969.5 1720.69  4975.7 1719.29
  4980.8 1719.94  4986.9 1718.08  4987.4 1717.58  4992.7 1718.08  5060.9 1719.00
  5094.5 1718.62  5154.1 1719.64  5192.8 1721.82  5268.2 1723.41  5729.5 1729.75
  5734.6 1731.12  5789.1 1731.36  5794.2 1732.64  5832.3 1733.49  6238.0 1738.47
#Mann=7,-1,0
  3745.0    0.05       0  3907.9     0.1       0  4423.1    0.05       0
  4726.3   0.075       0  4940.4    0.05       0  4986.9    0.03       0
  4992.7    0.05       0
Bank Sta=4986.9,4992.7
Exp/Cntr=0.3,0.1

Type RM Length L Ch R = 1,9629,334,334,334
BEGIN DESCRIPTION:
Elm 02 30 9629.31
END DESCRIPTION:
XS GIS Cut Line= 3
      1598104.48      6847864.69      1599559.33      6847691.08
      1600285.00      6847618.16
#Sta/Elev= 30
  3539.7 1733.26  3589.0 1732.49  3713.3 1731.45  3852.4 1729.99  3872.6 1726.63
  3945.9 1726.11  3994.1 1727.14  4147.1 1727.87  4312.1 1725.51  4386.2 1726.60
  4513.5 1724.89  4638.0 1723.15  4652.1 1722.34  4668.2 1718.87  4713.6 1719.09
  4768.9 1719.96  4970.3 1718.19  4989.1 1714.63  4989.6 1714.13  4995.0 1714.63
  5000.2 1716.83  5010.6 1717.90  5060.8 1720.61  5141.2 1720.32  5161.1 1721.54
  5282.5 1723.40  5422.6 1725.04  5512.5 1727.79  5687.4 1731.38  5734.2 1734.24
#Mann=12,-1,0
  3539.7     0.1       0  3589.0   0.075       0  3713.3     0.1       0
  3945.9   0.075       0  3994.1     0.1       0  4513.5    0.05       0
  4713.6   0.075       0  4989.1    0.07       0  4995.0   0.075       0
  5161.1    0.05       0  5282.5   0.075       0  5512.5    0.05       0
Bank Sta=4989.1,4995
Exp/Cntr=0.3,0.1

Type RM Length L Ch R = 1,9295,787,787,787
BEGIN DESCRIPTION:
Elm 02 30 9236.02
END DESCRIPTION:
XS GIS Cut Line= 3
      1598100.99      6848222.33      1599445.61      6847981.44
      1600010.77      6847925.97
#Sta/Elev= 30
  3587.1 1733.59  3631.8 1733.64  3682.6 1730.64  3723.2 1731.16  3814.9 1729.98
  3857.4 1731.04  3895.9 1731.41  3937.6 1728.93  4077.4 1727.50  4238.1 1724.70
  4292.2 1723.19  4347.8 1723.01  4461.4 1721.15  4564.4 1719.84  4617.3 1718.91
  4715.6 1719.41  4850.9 1714.66  4892.1 1717.06  4962.6 1715.52  4989.7 1712.29
  4990.2 1711.79  4995.7 1712.29  5012.8 1714.86  5083.1 1714.98  5173.6 1717.13
  5213.8 1719.28  5246.6 1719.03  5294.1 1720.53  5384.6 1726.06  5521.0 1729.30
#Mann=10,-1,0
  3587.1     0.1       0  3857.4   0.075       0  3937.6    0.05       0
  4077.4     0.1       0  4238.1   0.075       0  4347.8     0.1       0
  4461.4   0.075       0  4564.4    0.05       0  4989.7    0.03       0
  4995.7    0.05       0
Bank Sta=4989.7,4995.7
Exp/Cntr=0.3,0.1

Type RM Length L Ch R = 1,8508,666,666,666
BEGIN DESCRIPTION:
Elm 02 30 8508.27
END DESCRIPTION:
XS GIS Cut Line= 3
      1598292.01      6848910.98      1599401.34      6848713.07
      1600171.06      6848640.26
#Sta/Elev= 30
  3871.2 1729.60  3913.2 1728.22  3935.2 1728.92  3972.1 1726.20  4027.4 1725.62
  4097.7 1725.09  4118.0 1723.75  4209.4 1723.26  4300.9 1718.85  4374.6 1718.87
  4453.2 1715.89  4575.1 1714.79  4615.8 1712.57  4646.2 1712.10  4707.2 1713.56
  4798.6 1711.56  4920.5 1712.91  4951.0 1712.12  4968.1 1710.36  4968.6 1709.86
  4974.4 1710.36  5062.0 1713.17  5142.3 1713.86  5192.6 1718.03  5242.8 1719.79
  5363.3 1720.28  5383.4 1722.03  5504.0 1725.07  5684.8 1728.23  5771.2 1728.65
#Mann=4,-1,0
  3871.2   0.075       0  4027.4    0.05       0  4968.1    0.05       0
  4974.4    0.05       0
Bank Sta=4968.1,4974.4
Exp/Cntr=0.3,0.1

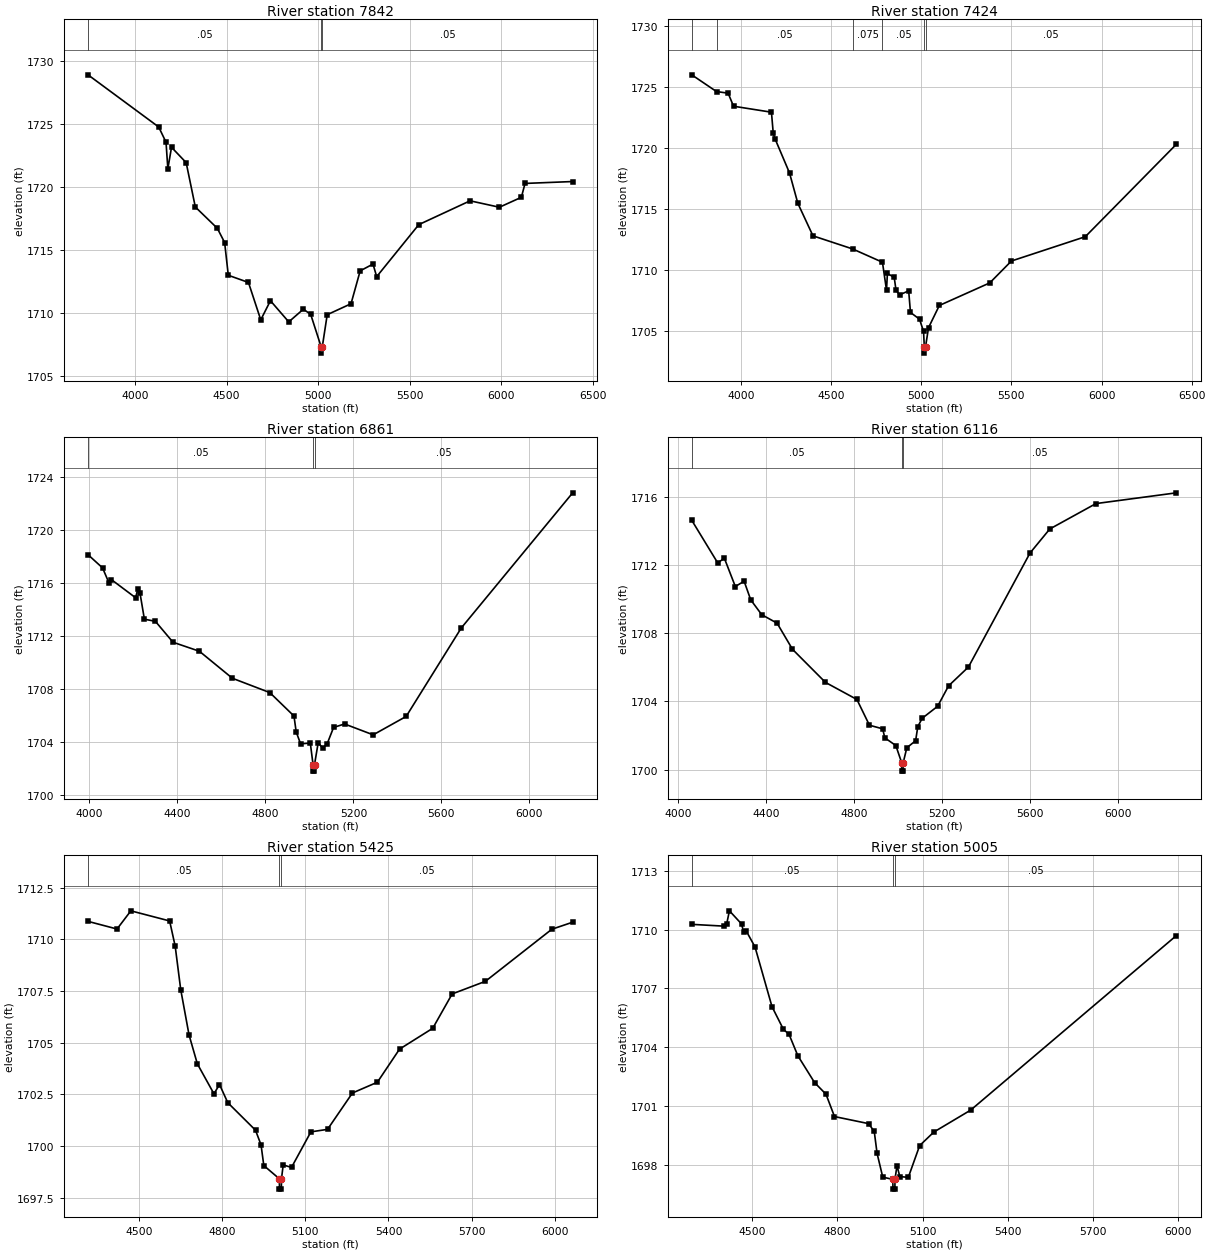
Type RM Length L Ch R = 1,7842,418,418,418
BEGIN DESCRIPTION:
Elm 02 30 7841.71
END DESCRIPTION:
XS GIS Cut Line= 3
      1598099.21      6849400.57      1599349.26      6849364.11
      1600745.06      6849322.44
#Sta/Elev= 30
  3743.6 1728.91  4129.6 1724.77  4169.6 1723.56  4179.6 1721.45  4199.6 1723.16
  4279.6 1721.94  4329.6 1718.42  4449.7 1716.73  4489.7 1715.60  4509.7 1713.00
  4619.8 1712.43  4687.0 1709.46  4739.8 1710.98  4839.9 1709.30  4919.9 1710.31
  4959.9 1709.89  5016.8 1707.32  5017.3 1706.82  5023.1 1707.32  5049.9 1709.87
  5180.0 1710.74  5230.0 1713.35  5300.1 1713.89  5320.1 1712.89  5550.2 1717.02
  5830.3 1718.91  5990.4 1718.40  6110.4 1719.19  6130.4 1720.29  6390.6 1720.44
#Mann=3,-1,0
  3743.6    0.05       0  5016.8    0.05       0  5023.1    0.05       0
Bank Sta=5016.8,5023.1
Exp/Cntr=0.3,0.1

Type RM Length L Ch R = 1,7424,563,563,563
BEGIN DESCRIPTION:
Elm 02 30 7424.28
END DESCRIPTION:
XS GIS Cut Line= 3
      1598083.64      6849858.90      1599364.88      6849780.78
      1600770.55      6849785.98
#Sta/Elev= 30
  3726.2 1725.99  3863.5 1724.62  3927.9 1724.49  3958.0 1723.42  4168.4 1722.93
  4178.4 1721.20  4188.4 1720.75  4268.6 1717.96  4314.9 1715.47  4398.8 1712.81
  4618.4 1711.74  4784.3 1710.65  4806.8 1708.37  4811.8 1709.73  4849.6 1709.41
  4859.7 1708.35  4879.7 1707.98  4929.8 1708.31  4939.8 1706.54  4989.9 1705.99
  5012.4 1704.99  5016.6 1703.71  5017.1 1703.21  5023.2 1703.71  5039.9 1705.29
  5099.9 1707.11  5379.9 1708.96  5499.9 1710.75  5909.9 1712.74  6415.5 1720.31
#Mann=6,-1,0
  3726.2   0.075       0  3863.5    0.05       0  4618.4   0.075       0
  4784.3    0.05       0  5016.6    0.03       0  5023.2    0.05       0
Bank Sta=5016.6,5023.2
Exp/Cntr=0.3,0.1

Type RM Length L Ch R = 1,6861,745,745,745
BEGIN DESCRIPTION:
Elm 02 30 6860.88
END DESCRIPTION:
XS GIS Cut Line= 3
      1598348.78      6850358.60      1599359.19      6850344.72
      1600551.81      6850330.85
#Sta/Elev= 30
  3993.6 1718.13  4059.8 1717.13  4089.8 1715.96  4099.8 1716.25  4209.8 1714.88
  4219.8 1715.52  4229.8 1715.24  4249.8 1713.26  4299.8 1713.10  4379.9 1711.52
  4499.9 1710.84  4649.9 1708.80  4819.9 1707.72  4929.9 1705.95  4939.9 1704.75
  4959.9 1703.85  5004.1 1703.91  5016.5 1702.29  5017.0 1701.79  5022.8 1701.79
  5023.3 1702.29  5039.9 1703.94  5059.9 1703.54  5079.9 1703.82  5109.9 1705.09
  5159.9 1705.35  5289.9 1704.53  5439.9 1705.92  5690.0 1712.59  6196.8 1722.80
#Mann=3,-1,0
  3993.6    0.05       0  5016.5    0.03       0  5023.3    0.05       0
Bank Sta=5016.5,5023.3
Exp/Cntr=0.3,0.1

Type RM Length L Ch R = 1,6116,691,691,691
BEGIN DESCRIPTION:
Elm 02 30 6116.17
END DESCRIPTION:
XS GIS Cut Line= 3
      1598416.86      6851106.87      1599354.33      6851089.51
      1600620.82      6851051.34
#Sta/Elev= 30
  4061.6 1714.61  4179.8 1712.11  4209.8 1712.39  4259.8 1710.73  4299.8 1711.04
  4329.8 1709.95  4379.8 1709.08  4449.8 1708.58  4519.8 1707.05  4669.8 1705.11
  4812.8 1704.11  4869.9 1702.60  4929.9 1702.39  4939.9 1701.86  4989.9 1701.41
  5016.3 1700.41  5016.8 1699.91  5023.1 1699.91  5023.6 1700.41  5039.9 1701.28
  5079.9 1701.69  5089.9 1702.52  5110.0 1703.01  5180.0 1703.71  5230.0 1704.91
  5320.1 1706.01  5600.2 1712.69  5690.2 1714.10  5900.3 1715.59  6266.3 1716.22
#Mann=3,-1,0
  4061.6    0.05       0  5016.3    0.05       0  5023.6    0.05       0
Bank Sta=5016.3,5023.6
Exp/Cntr=0.3,0.1

Type RM Length L Ch R = 1,5425,420,420,420
BEGIN DESCRIPTION:
Elm 02 30 5425.21
END DESCRIPTION:
XS GIS Cut Line= 3
      1598670.31      6851783.95      1599350.86      6851780.48
      1600420.15      6851770.06
#Sta/Elev= 30
  4315.2 1710.87  4419.9 1710.50  4469.9 1711.38  4609.9 1710.89  4629.9 1709.67
  4649.9 1707.57  4679.9 1705.38  4709.9 1703.98  4769.9 1702.53  4789.9 1702.98
  4819.9 1702.10  4919.9 1700.77  4939.9 1700.06  4949.9 1699.06  5006.0 1698.42
  5006.5 1697.92  5013.2 1697.92  5013.7 1698.42  5019.9 1699.09  5049.9 1698.97
  5119.9 1700.69  5179.9 1700.81  5269.9 1702.57  5359.9 1703.09  5439.9 1704.69
  5559.9 1705.70  5629.9 1707.36  5749.9 1707.97  5989.9 1710.49  6065.1 1710.83
#Mann=3,-1,0
  4315.2    0.05       0  5006.0    0.05       0  5013.7    0.05       0
Bank Sta=5006,5013.7
Exp/Cntr=0.3,0.1

Type RM Length L Ch R = 1,5005,221,221,221
BEGIN DESCRIPTION:
Elm 02 30 5005.18
END DESCRIPTION:
XS GIS Cut Line= 3
      1598642.33      6852164.19      1599358.50      6852200.65
      1600350.32      6852213.66
#Sta/Elev= 30
  4286.3 1710.27  4399.1 1710.18  4409.1 1710.27  4419.1 1710.96  4461.9 1710.29
  4469.2 1709.87  4479.2 1709.91  4509.3 1709.12  4569.3 1706.07  4609.4 1704.92
  4629.4 1704.66  4660.4 1703.57  4719.5 1702.20  4759.6 1701.61  4789.6 1700.47
  4909.8 1700.11  4929.8 1699.71  4939.8 1698.59  4959.8 1697.38  4995.3 1697.27
  4995.8 1696.77  5002.5 1696.77  5003.0 1697.27  5009.9 1697.97  5019.9 1697.41
  5049.9 1697.37  5089.9 1698.99  5139.9 1699.68  5269.9 1700.80  5995.3 1709.70
#Mann=3,-1,0
  4286.3    0.05       0  4995.3    0.03       0  5003.0    0.05       0
Bank Sta=4995.3,5003
Exp/Cntr=0.3,0.1

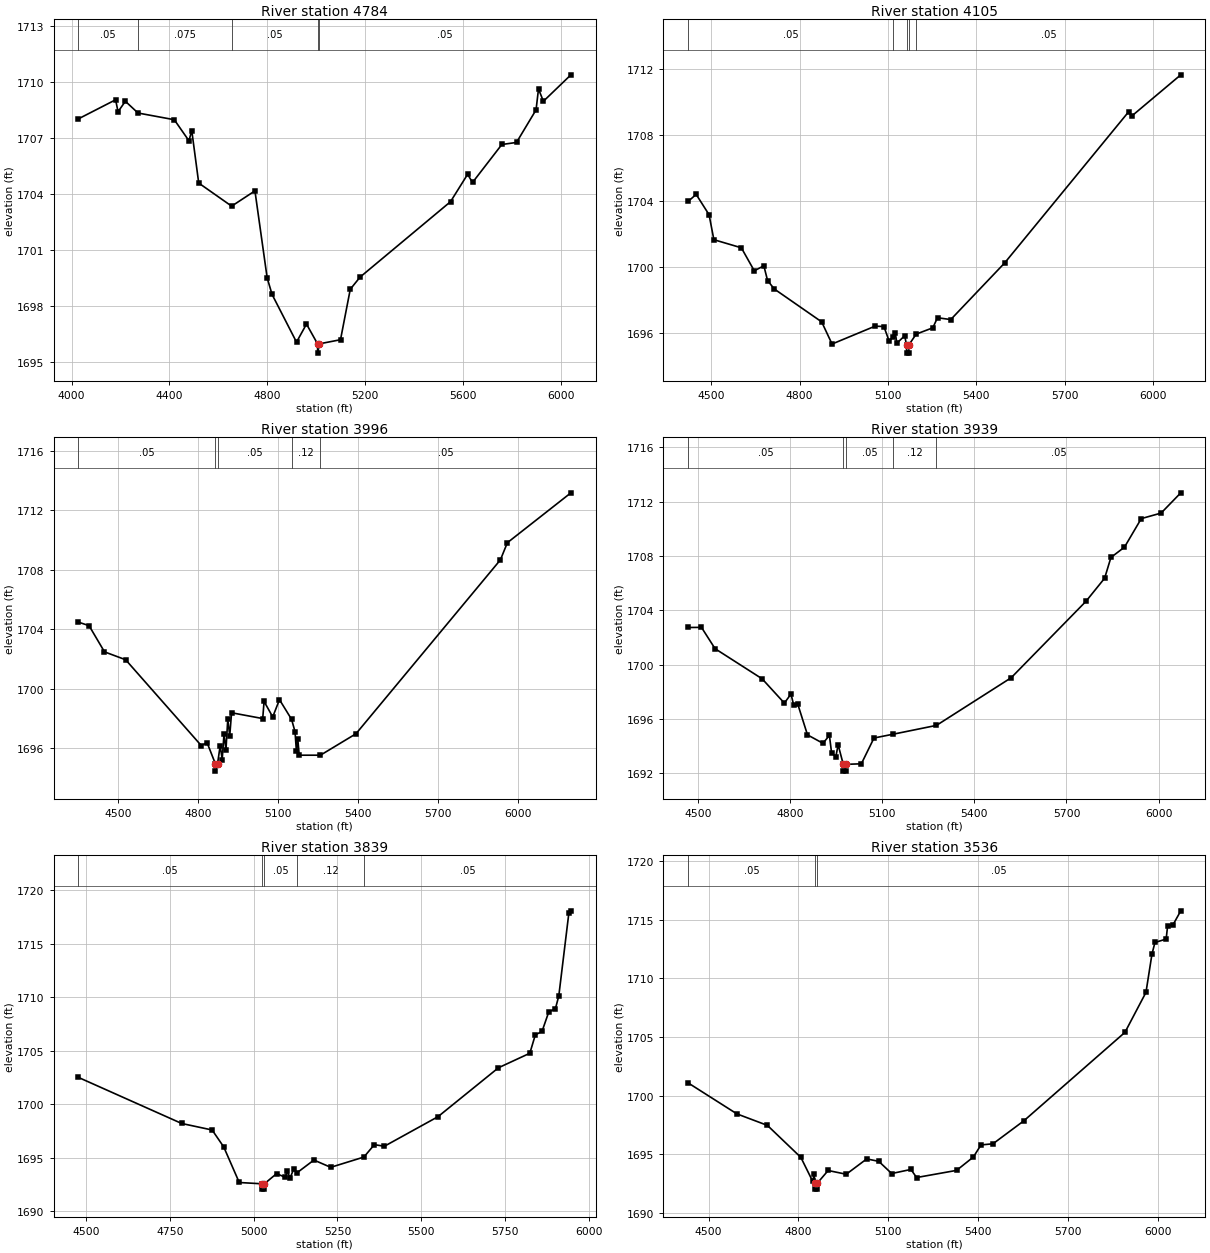
Type RM Length L Ch R = 1,4784,679,679,679
BEGIN DESCRIPTION:
Elm 02 30 4783.58
END DESCRIPTION:
XS GIS Cut Line= 3
      1598381.93      6852442.84      1599358.50      6852422.00
      1600397.59      6852437.63
#Sta/Elev= 30
  4026.6 1708.03  4179.7 1709.06  4189.7 1708.42  4219.7 1708.98  4271.4 1708.35
  4419.8 1707.99  4479.8 1706.86  4491.3 1707.41  4519.8 1704.59  4654.5 1703.35
  4749.8 1704.17  4799.8 1699.50  4819.9 1698.61  4919.9 1696.05  4960.7 1697.02
  5005.9 1695.96  5006.4 1695.46  5013.8 1695.96  5099.9 1696.18  5139.9 1698.89
  5179.9 1699.54  5550.0 1703.59  5620.0 1705.06  5640.0 1704.62  5760.0 1706.66
  5820.0 1706.77  5900.0 1708.52  5910.0 1709.64  5930.0 1708.98  6042.6 1710.40
#Mann=5,-1,0
  4026.6    0.05       0  4271.4   0.075       0  4654.5    0.05       0
  5005.9    0.05       0  5013.8    0.05       0
Bank Sta=5005.9,5013.8
Exp/Cntr=0.3,0.1

Type RM Length L Ch R = 1,4105,109,109,109
BEGIN DESCRIPTION:
Elm 02 30 4105.22
END DESCRIPTION:
XS GIS Cut Line= 5
      1598716.99      6852739.27      1599071.17      6852929.38
      1599211.80      6853041.36      1599315.96      6853046.57
      1600289.93      6852885.11
#Sta/Elev= 30
  4421.3 1703.96  4448.9 1704.39  4492.7 1703.16  4509.0 1701.65  4602.3 1701.16
  4646.2 1699.77  4678.7 1700.07  4691.4 1699.18  4714.1 1698.67  4875.1 1696.68
  4910.3 1695.34  5056.3 1696.42  5086.4 1696.40  5104.4 1695.51  5117.6 1695.79
  5125.4 1695.98  5130.4 1695.39  5157.0 1695.84  5163.2 1695.29  5163.7 1694.79
  5170.7 1694.79  5171.2 1695.29  5196.1 1695.94  5252.4 1696.32  5268.5 1696.93
  5313.4 1696.82  5496.3 1700.24  5917.3 1709.38  5928.3 1709.13  6094.6 1711.62
#Mann=5,-1,0
  4421.3    0.05       0  5117.6    0.12       0  5163.2    0.05       0
  5171.2    0.12       0  5196.1    0.05       0
Bank Sta=5163.2,5171.2
Exp/Cntr=0.3,0.1

Type RM Length L Ch R = 1,3996,57,57,57
BEGIN DESCRIPTION:
Elm 02 30 3995.95
END DESCRIPTION:
XS GIS Cut Line= 6
      1598637.10      6852760.52      1599053.81      6853015.75
      1599165.79      6853138.15      1599233.50      6853145.96
      1599319.43      6853114.71      1600340.14      6852937.65
#Sta/Elev= 30
  4350.0 1704.49  4390.8 1704.25  4448.8 1702.49  4528.2 1701.96  4812.5 1696.19
  4833.8 1696.40  4865.0 1694.98  4865.5 1694.48  4873.3 1694.98  4883.3 1696.20
  4890.7 1695.26  4897.5 1696.96  4904.9 1695.91  4911.7 1697.97  4919.1 1696.85
  4925.9 1698.40  5042.9 1698.01  5048.0 1699.16  5080.5 1698.12  5105.8 1699.28
  5151.2 1697.96  5164.2 1697.13  5169.4 1695.82  5174.5 1696.64  5180.0 1695.55
  5259.6 1695.55  5393.1 1696.99  5935.4 1708.67  5961.5 1709.82  6200.1 1713.17
#Mann=5,-1,0
  4350.0    0.05       0  4865.0    0.05       0  4873.3    0.05       0
  5151.2    0.12       0  5259.6    0.05       0
Bank Sta=4865,4873.3
Exp/Cntr=0.3,0.1

Type RM Length L Ch R = 1,3939,100,100,100
BEGIN DESCRIPTION:
Elm 02 30 3938.66
END DESCRIPTION:
XS GIS Cut Line= 5
      1598683.17      6852955.43      1599052.94      6853101.26
      1599151.90      6853189.80      1599235.23      6853210.63
      1600209.16      6853041.37
#Sta/Elev= 30
  4467.5 1702.74  4511.2 1702.75  4555.5 1701.18  4708.8 1698.96  4781.2 1697.17
  4802.7 1697.84  4811.7 1697.01  4824.2 1697.14  4856.5 1694.83  4906.9 1694.21
  4927.9 1694.79  4934.8 1693.53  4948.8 1693.22  4956.3 1694.10  4973.0 1692.66
  4973.5 1692.16  4980.8 1692.16  4981.3 1692.66  5031.9 1692.70  5073.1 1694.60
  5135.5 1694.88  5276.6 1695.53  5519.9 1699.04  5763.5 1704.67  5824.2 1706.37
  5844.7 1707.90  5888.9 1708.66  5943.5 1710.76  6008.2 1711.17  6072.2 1712.66
#Mann=5,-1,0
  4467.5    0.05       0  4973.0    0.05       0  4981.3    0.05       0
  5135.5    0.12       0  5276.6    0.05       0
Bank Sta=4973,4981.3
Exp/Cntr=0.3,0.1

Type RM Length L Ch R = 1,3839,303,303,303
BEGIN DESCRIPTION:
Mapping XS eab36b28
END DESCRIPTION:
XS GIS Cut Line= 4
      1598597.08      6853217.16      1598939.13      6853248.42
      1599310.66      6853309.18      1600061.17      6853265.85
#Sta/Elev= 30
  4475.5 1702.51  4784.7 1698.19  4875.6 1697.58  4910.2 1696.00  4956.6 1692.67
  5023.4 1692.55  5023.9 1692.05  5031.2 1692.05  5031.7 1692.55  5068.1 1693.50
  5094.3 1693.15  5099.4 1693.74  5108.6 1693.11  5118.8 1693.89  5129.2 1693.58
  5179.6 1694.77  5229.8 1694.09  5328.9 1695.05  5360.1 1696.21  5390.1 1696.06
  5550.4 1698.83  5730.7 1703.40  5824.5 1704.76  5840.9 1706.48  5860.9 1706.80
  5880.9 1708.61  5901.0 1708.94  5911.0 1710.12  5941.0 1717.86  5947.2 1718.08
#Mann=5,-1,0
  4475.5    0.05       0  5023.4    0.05       0  5031.7    0.05       0
  5129.2    0.12       0  5328.9    0.05       0
Bank Sta=5023.4,5031.7
Exp/Cntr=0.3,0.1

Type RM Length L Ch R = 1,3536,73,73,73
BEGIN DESCRIPTION:
Mapping XS a6bcbd56
END DESCRIPTION:
XS GIS Cut Line= 6
      1598614.49      6853477.59      1599098.85      6853564.39
      1599213.44      6853552.24      1599242.95      6853422.03
      1599449.55      6853373.42      1600141.10      6853330.09
#Sta/Elev= 30
  4431.3 1701.08  4594.6 1698.43  4696.4 1697.45  4808.1 1694.72  4847.8 1692.67
  4852.9 1693.30  4854.6 1692.51  4855.1 1692.01  4862.4 1692.01  4862.9 1692.51
  4899.3 1693.60  4959.8 1693.28  5028.3 1694.59  5068.5 1694.38  5111.6 1693.34
  5175.8 1693.69  5194.8 1693.00  5328.4 1693.61  5384.4 1694.75  5409.9 1695.78
  5450.0 1695.88  5553.1 1697.84  5890.8 1705.39  5961.0 1708.80  5981.0 1712.06
  5991.0 1713.06  6028.4 1713.35  6033.4 1714.48  6051.1 1714.56  6077.3 1715.76
#Mann=3,-1,0
  4431.3    0.05       0  4854.6    0.05       0  4862.9    0.05       0
Bank Sta=4854.6,4862.9
Exp/Cntr=0.3,0.1