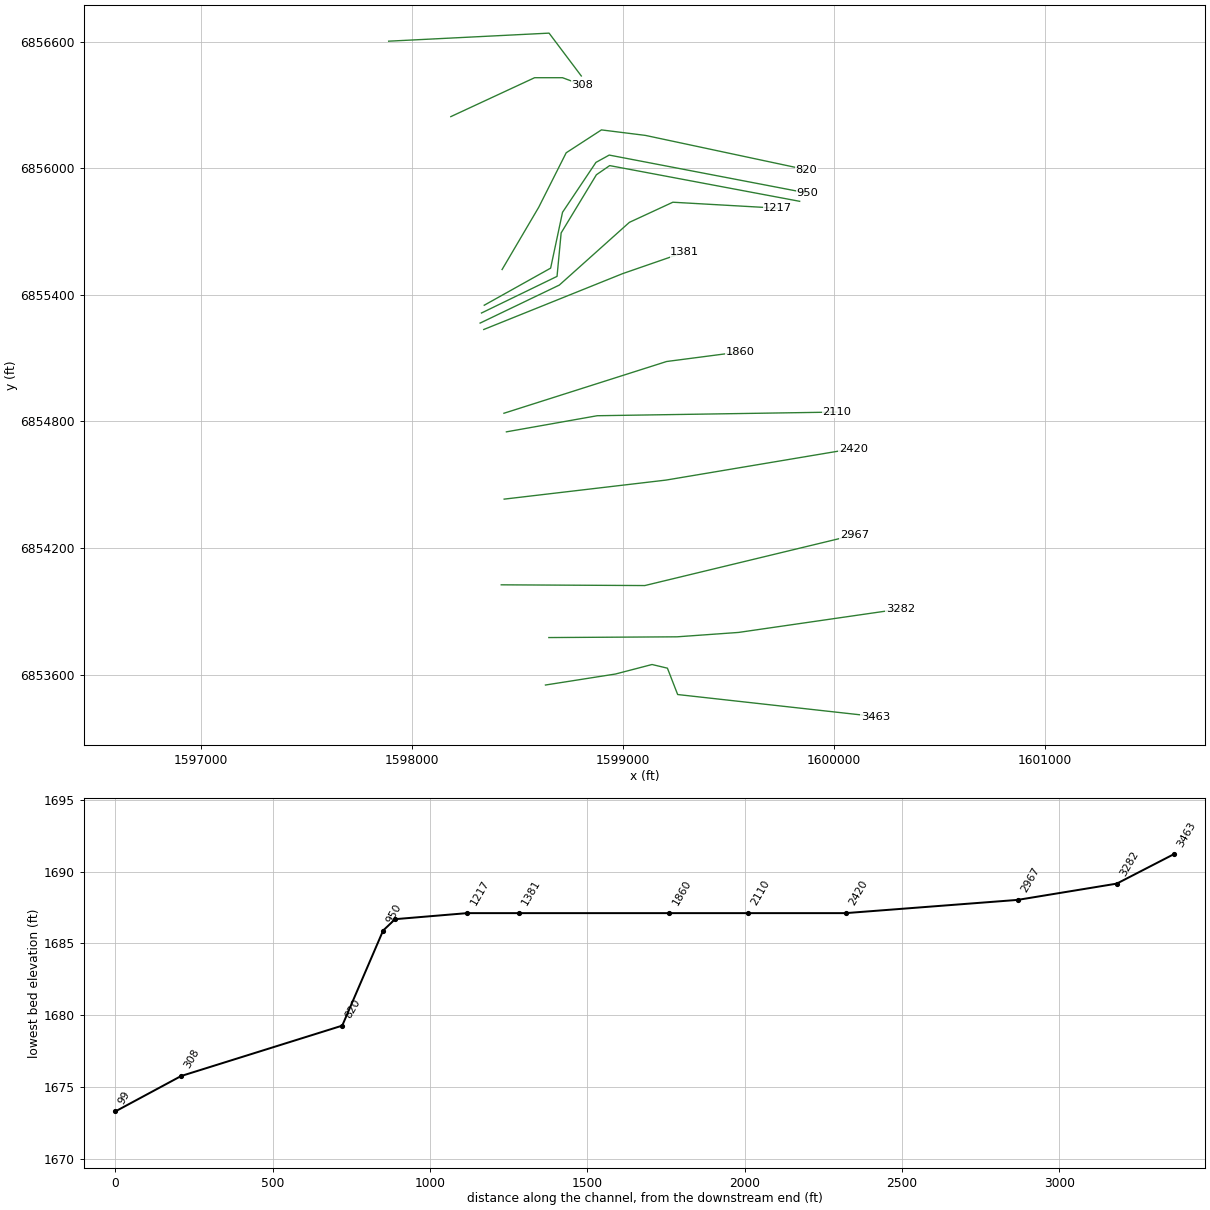
HEC-RAS study Elm 02 30.prj: Elm 02 30 Base Level Engineering

--- Elm 02 30.g01 (geometry) --- (continued)

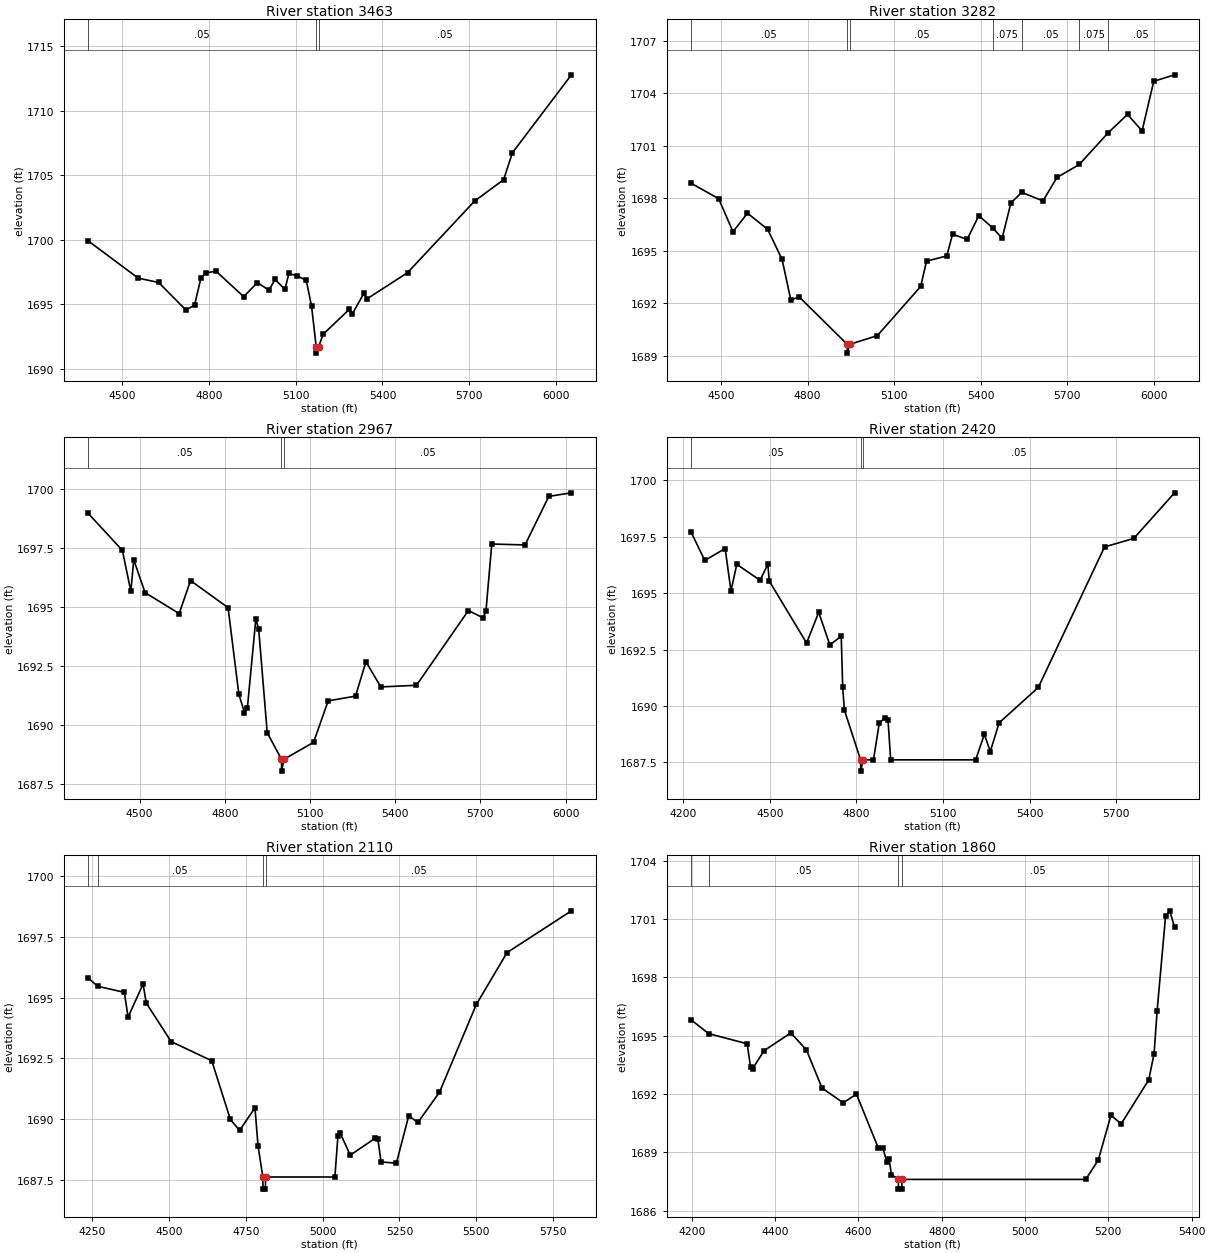
Type RM Length L Ch R = 1,3463,181,181,181
BEGIN DESCRIPTION:
Mapping XS eeeea8b1
END DESCRIPTION:
XS GIS Cut Line= 6
      1598633.56      6853550.50      1598965.17      6853602.58
      1599138.79      6853647.72      1599211.70      6853630.36
      1599260.31      6853505.36      1600197.79      6853401.20
#Sta/Elev= 30
  4381.9 1699.92  4555.4 1697.02  4626.3 1696.68  4720.7 1694.54  4750.4 1694.93
  4772.5 1697.03  4789.5 1697.43  4824.9 1697.55  4920.3 1695.58  4967.6 1696.67
  5007.6 1696.08  5028.8 1696.92  5062.8 1696.14  5076.5 1697.38  5105.4 1697.19
  5136.6 1696.85  5155.0 1694.83  5170.9 1691.70  5171.4 1691.20  5179.2 1691.70
  5195.2 1692.67  5285.6 1694.60  5295.7 1694.24  5335.9 1695.84  5345.9 1695.40
  5486.7 1697.44  5718.3 1702.99  5819.0 1704.66  5849.2 1706.74  6053.3 1712.79
#Mann=3,-1,0
  4381.9    0.05       0  5170.9    0.05       0  5179.2    0.05       0
Bank Sta=5170.9,5179.2
Exp/Cntr=0.3,0.1

Type RM Length L Ch R = 1,3282,315,315,315
BEGIN DESCRIPTION:
Elm 02 30 3282.48
END DESCRIPTION:
XS GIS Cut Line= 4
      1598649.60      6853775.50      1599257.27      6853778.98
      1599548.93      6853799.81      1600316.34      6853910.93
#Sta/Elev= 30
  4396.4 1698.86  4491.8 1697.98  4541.8 1696.09  4591.8 1697.15  4661.8 1696.23
  4711.8 1694.51  4741.8 1692.21  4771.8 1692.36  4937.6 1689.66  4938.1 1689.16
  4946.0 1689.66  5041.9 1690.16  5192.3 1692.97  5212.3 1694.41  5282.5 1694.71
  5302.6 1695.95  5353.1 1695.65  5393.6 1697.01  5442.8 1696.29  5474.4 1695.72
  5504.7 1697.73  5542.4 1698.34  5615.9 1697.85  5664.5 1699.19  5741.7 1699.93
  5841.3 1701.73  5908.9 1702.79  5959.4 1701.85  5999.8 1704.68  6071.9 1705.05
#Mann=7,-1,0
  4396.4    0.05       0  4937.6    0.05       0  4946.0    0.05       0
  5442.8   0.075       0  5542.4    0.05       0  5741.7   0.075       0
  5841.3    0.05       0
Bank Sta=4937.6,4946
Exp/Cntr=0.3,0.1

Type RM Length L Ch R = 1,2967,547,547,547
BEGIN DESCRIPTION:
Elm 02 30 2966.85
END DESCRIPTION:
XS GIS Cut Line= 3
      1598423.94      6854025.50      1599104.49      6854022.03
      1600097.54      6854261.61
#Sta/Elev= 30
  4318.5 1698.97  4439.6 1697.39  4469.6 1695.65  4479.6 1696.99  4519.6 1695.60
  4639.6 1694.71  4679.6 1696.11  4811.8 1694.96  4849.6 1691.30  4869.6 1690.51
  4879.6 1690.69  4909.6 1694.49  4919.6 1694.04  4949.6 1689.66  4999.8 1688.53
  5000.3 1688.03  5008.2 1688.53  5112.7 1689.25  5164.2 1691.01  5260.5 1691.21
  5297.2 1692.67  5349.4 1691.60  5475.1 1691.67  5657.9 1694.84  5709.4 1694.53
  5719.7 1694.82  5740.2 1697.66  5857.2 1697.62  5941.0 1699.68  6020.6 1699.83
#Mann=3,-1,0
  4318.5    0.05       0  4999.8    0.05       0  5008.2    0.05       0
Bank Sta=4999.8,5008.2
Exp/Cntr=0.3,0.1

Type RM Length L Ch R = 1,2420,310,310,310
BEGIN DESCRIPTION:
Elm 02 30 2420.38
END DESCRIPTION:
XS GIS Cut Line= 3
      1598437.83      6854431.75      1599205.18      6854522.03
      1600094.09      6854671.34
#Sta/Elev= 30
  4227.6 1697.71  4275.1 1696.45  4345.6 1696.98  4365.7 1695.10  4385.9 1696.28
  4466.4 1695.57  4493.3 1696.28  4498.3 1695.54  4627.5 1692.79  4669.5 1694.15
  4708.1 1692.71  4747.5 1693.09  4752.6 1690.82  4758.4 1689.82  4814.5 1687.61
  4815.0 1687.11  4823.2 1687.61  4859.1 1687.61  4879.2 1689.24  4899.4 1689.48
  4909.4 1689.39  4918.7 1687.61  5213.0 1687.61  5243.0 1688.74  5263.7 1687.98
  5294.1 1689.25  5429.8 1690.82  5659.2 1697.05  5760.6 1697.43  5901.6 1699.45
#Mann=3,-1,0
  4227.6    0.05       0  4814.5    0.03       0  4823.2    0.05       0
Bank Sta=4814.5,4823.2
Exp/Cntr=0.3,0.1

Type RM Length L Ch R = 1,2110,250,250,250
BEGIN DESCRIPTION:
Mapping XS 7bf1696e
END DESCRIPTION:
XS GIS Cut Line= 3
      1598448.42      6854750.74      1598878.95      6854827.12
      1600014.37      6854844.48
#Sta/Elev= 30
  4236.8 1695.82  4268.5 1695.47  4355.2 1695.22  4367.3 1694.20  4416.1 1695.56
  4426.4 1694.78  4507.5 1693.19  4639.6 1692.40  4700.1 1689.98  4730.1 1689.53
  4780.1 1690.46  4790.1 1688.89  4805.7 1687.61  4806.2 1687.11  4814.1 1687.11
  4814.6 1687.61  5040.1 1687.61  5050.1 1689.32  5056.9 1689.43  5090.1 1688.51
  5170.2 1689.20  5180.2 1689.16  5190.2 1688.23  5240.2 1688.18  5280.2 1690.13
  5310.2 1689.86  5380.2 1691.10  5500.2 1694.72  5600.2 1696.86  5809.6 1698.58
#Mann=4,-1,0
  4236.8   0.075       0  4268.5    0.05       0  4805.7    0.03       0
  4814.6    0.05       0
Bank Sta=4805.7,4814.6
Exp/Cntr=0.3,0.1

Type RM Length L Ch R = 1,1860,479,479,479
BEGIN DESCRIPTION:
Elm 02 30 1860.73
END DESCRIPTION:
XS GIS Cut Line= 3
      1598436.68      6854838.84      1599207.96      6855084.18
      1599556.45      6855129.63
#Sta/Elev= 30
  4198.1 1695.82  4240.4 1695.11  4332.8 1694.59  4340.9 1693.39  4346.1 1693.31
  4373.1 1694.23  4437.6 1695.15  4475.1 1694.27  4512.6 1692.31  4563.6 1691.55
  4595.1 1692.00  4647.6 1689.23  4658.1 1689.24  4668.5 1688.51  4673.7 1688.65
  4679.1 1687.86  4695.6 1687.61  4696.1 1687.11  4704.0 1687.11  4704.5 1687.61
  5145.7 1687.61  5175.9 1688.61  5206.2 1690.91  5230.8 1690.47  5296.9 1692.73
  5309.8 1694.08  5317.1 1696.29  5337.3 1701.15  5347.4 1701.43  5358.9 1700.59
#Mann=4,-1,0
  4198.1   0.075       0  4240.4    0.05       0  4695.6    0.03       0
  4704.5    0.05       0
Bank Sta=4695.6,4704.5
Exp/Cntr=0.3,0.1

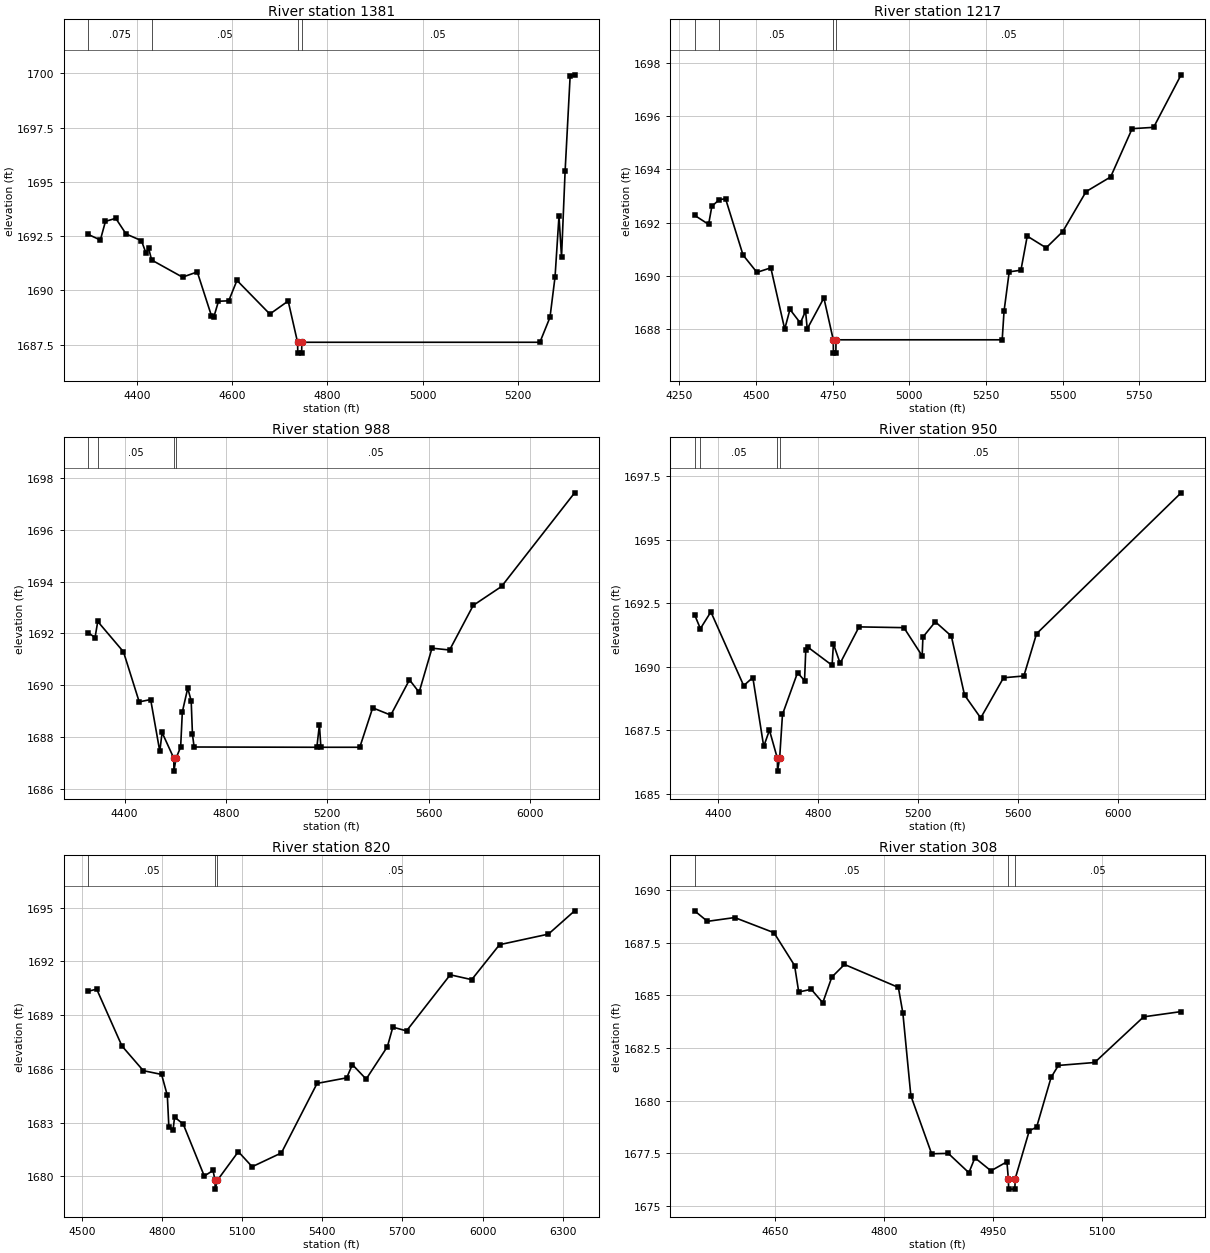
Type RM Length L Ch R = 1,1381,164,164,164
BEGIN DESCRIPTION:
Elm 02 30 1381.05
END DESCRIPTION:
XS GIS Cut Line= 3
      1598341.19      6855235.98      1598999.63      6855500.85
      1599293.87      6855602.73
#Sta/Elev= 30
  4298.0 1692.58  4323.7 1692.32  4334.4 1693.18  4356.0 1693.32  4377.6 1692.60
  4409.9 1692.29  4419.6 1691.71  4425.0 1691.94  4431.3 1691.40  4496.1 1690.61
  4527.1 1690.85  4556.7 1688.84  4562.1 1688.79  4571.6 1689.50  4593.1 1689.52
  4610.4 1690.46  4679.4 1688.91  4717.9 1689.51  4737.6 1687.61  4738.1 1687.11
  4746.1 1687.11  4746.6 1687.61  5246.2 1687.61  5267.4 1688.76  5278.0 1690.62
  5286.3 1693.43  5291.6 1691.53  5299.1 1695.48  5309.7 1699.88  5319.1 1699.93
#Mann=4,-1,0
  4298.0   0.075       0  4431.3    0.05       0  4737.6    0.03       0
  4746.6    0.05       0
Bank Sta=4737.6,4746.6
Exp/Cntr=0.3,0.1

Type RM Length L Ch R = 1,1217,229,229,229
BEGIN DESCRIPTION:
Mapping XS cbbeec5a
END DESCRIPTION:
XS GIS Cut Line= 5
      1598323.82      6855266.35      1598699.26      6855446.48
      1599031.29      6855743.79      1599237.45      6855839.27
      1599734.45      6855811.06
#Sta/Elev= 30
  4299.3 1692.28  4345.0 1691.94  4355.7 1692.62  4380.2 1692.87  4400.4 1692.90
  4457.4 1690.79  4502.7 1690.14  4548.0 1690.31  4593.3 1688.01  4610.4 1688.75
  4644.4 1688.24  4661.3 1688.69  4666.8 1688.02  4721.1 1689.18  4751.7 1687.61
  4752.2 1687.11  4760.2 1687.11  4760.7 1687.61  5302.8 1687.61  5308.8 1688.68
  5325.7 1690.16  5363.9 1690.22  5384.5 1691.50  5446.2 1691.06  5500.3 1691.67
  5576.5 1693.17  5656.6 1693.72  5726.7 1695.53  5796.8 1695.58  5886.4 1697.55
#Mann=4,-1,0
  4299.3   0.075       0  4380.2    0.05       0  4751.7    0.03       0
  4760.7    0.05       0
Bank Sta=4751.7,4760.7
Exp/Cntr=0.3,0.1

Type RM Length L Ch R = 1,988,38,38,38
BEGIN DESCRIPTION:
Mapping XS e0d883cd
END DESCRIPTION:
XS GIS Cut Line= 6
      1598330.33      6855314.10      1598688.41      6855487.71
      1598707.94      6855693.87      1598875.04      6855969.48
      1598937.98      6856012.88      1599838.62      6855843.61
#Sta/Elev= 30
  4256.0 1692.03  4283.4 1691.84  4294.0 1692.46  4395.6 1691.29  4457.7 1689.36
  4502.9 1689.45  4539.0 1687.45  4548.0 1688.18  4594.2 1687.19  4594.7 1686.69
  4603.2 1687.19  4621.3 1687.62  4627.9 1688.97  4649.3 1689.89  4662.9 1689.40
  4667.9 1688.11  4674.4 1687.62  5159.0 1687.61  5169.1 1688.48  5174.9 1687.61
  5328.5 1687.61  5379.4 1689.13  5450.8 1688.85  5524.6 1690.21  5562.7 1689.73
  5613.5 1691.43  5683.1 1691.36  5776.3 1693.08  5888.1 1693.81  6176.6 1697.42
#Mann=4,-1,0
  4256.0   0.075       0  4294.0    0.05       0  4594.2    0.03       0
  4603.2    0.05       0
Bank Sta=4594.2,4603.2
Exp/Cntr=0.3,0.1

Type RM Length L Ch R = 1,950,130,130,130
BEGIN DESCRIPTION:
Mapping XS 1529cea4
END DESCRIPTION:
XS GIS Cut Line= 6
      1598343.39      6855351.01      1598658.03      6855526.77
      1598714.45      6855791.53      1598872.87      6856028.07
      1598935.80      6856062.80      1599874.55      6855882.84
#Sta/Elev= 30
  4306.6 1692.05  4329.8 1691.50  4371.8 1692.16  4503.2 1689.26  4539.8 1689.58
  4583.4 1686.87  4606.3 1687.51  4638.1 1686.40  4638.6 1685.90  4647.1 1686.40
  4658.5 1688.13  4718.8 1689.77  4746.8 1689.46  4751.8 1690.67  4759.2 1690.78
  4857.1 1690.06  4862.4 1690.90  4889.3 1690.14  4965.0 1691.57  5144.6 1691.54
  5217.7 1690.43  5220.7 1691.17  5270.4 1691.77  5334.5 1691.21  5387.3 1688.89
  5452.1 1687.99  5543.5 1689.57  5624.8 1689.64  5675.6 1691.30  6254.3 1696.84
#Mann=4,-1,0
  4306.6   0.075       0  4329.8    0.05       0  4638.1    0.05       0
  4647.1    0.05       0
Bank Sta=4638.1,4647.1
Exp/Cntr=0.3,0.1

Type RM Length L Ch R = 1,820,512,512,512
BEGIN DESCRIPTION:
Mapping XS 4d44b19c
END DESCRIPTION:
XS GIS Cut Line= 6
      1598428.01      6855520.29      1598601.60      6855815.40
      1598731.81      6856073.65      1598898.91      6856182.15
      1599107.25      6856156.11      1599870.52      6855993.48
#Sta/Elev= 30
  4523.6 1690.33  4555.7 1690.45  4650.1 1687.28  4730.2 1685.90  4798.6 1685.69
  4820.1 1684.52  4825.9 1682.75  4841.5 1682.58  4847.3 1683.31  4879.6 1682.92
  4958.5 1680.02  4991.1 1680.33  4998.7 1679.79  4999.2 1679.29  5007.8 1679.79
  5085.9 1681.38  5137.7 1680.54  5247.1 1681.31  5380.7 1685.19  5491.6 1685.50
  5512.8 1686.24  5564.4 1685.43  5643.9 1687.24  5664.3 1688.33  5715.5 1688.12
  5879.1 1691.25  5959.5 1690.98  6063.7 1692.93  6246.6 1693.52  6344.8 1694.82
#Mann=3,-1,0
  4523.6    0.05       0  4998.7    0.03       0  5007.8    0.05       0
Bank Sta=4998.7,5007.8
Exp/Cntr=0.3,0.1

Type RM Length L Ch R = 1,308,209,209,209
BEGIN DESCRIPTION:
Mapping XS d5c3ea5e
END DESCRIPTION:
XS GIS Cut Line= 4
      1598184.90      6856245.07      1598582.07      6856429.55
      1598714.45      6856429.55      1598807.80      6856394.82
#Sta/Elev= 30
  4539.2 1689.02  4556.9 1688.52  4594.4 1688.70  4648.5 1687.98  4676.9 1686.42
  4682.6 1685.16  4699.8 1685.29  4715.7 1684.65  4728.2 1685.87  4745.6 1686.47
  4819.8 1685.38  4826.0 1684.16  4837.0 1680.23  4865.6 1677.47  4888.5 1677.49
  4916.9 1676.57  4925.2 1677.28  4947.3 1676.66  4969.3 1677.09  4971.2 1676.29
  4971.7 1675.79  4980.2 1675.79  4980.7 1676.29  5000.1 1678.57  5010.1 1678.73
  5030.1 1681.10  5040.1 1681.67  5090.1 1681.81  5157.5 1683.98  5209.1 1684.23
#Mann=3,-1,0
  4539.2    0.05       0  4971.2    0.03       0  4980.7    0.05       0
Bank Sta=4971.2,4980.7
Exp/Cntr=0.3,0.1

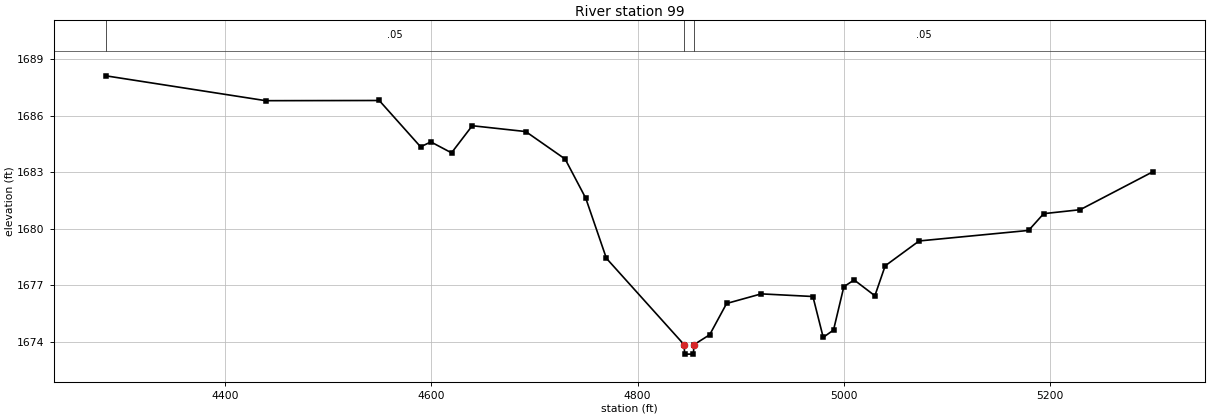
Type RM Length L Ch R = 1,99,0,0,0
BEGIN DESCRIPTION:
Elm 02 30 577.312
END DESCRIPTION:
XS GIS Cut Line= 3
      1597890.18      6856602.73      1598650.65      6856640.92
      1598803.43      6856437.79
#Sta/Elev= 30
  4284.3 1688.11  4439.3 1686.79  4549.4 1686.80  4589.5 1684.34  4599.5 1684.60
  4619.5 1684.02  4639.6 1685.46  4691.5 1685.15  4729.7 1683.69  4749.7 1681.61
  4769.7 1678.42  4845.1 1673.83  4845.6 1673.33  4854.1 1673.33  4854.6 1673.83
  4869.9 1674.36  4886.3 1676.02  4919.9 1676.53  4970.0 1676.39  4980.0 1674.22
  4990.0 1674.61  5000.0 1676.91  5010.0 1677.27  5030.1 1676.43  5040.1 1678.02
  5073.0 1679.34  5179.2 1679.90  5193.8 1680.79  5229.2 1681.00  5299.9 1683.02
#Mann=3,-1,0
  4284.3    0.05       0  4845.1    0.03       0  4854.6    0.05       0
Bank Sta=4845.1,4854.6
Exp/Cntr=0.3,0.1

Chan Stop Cuts=-1