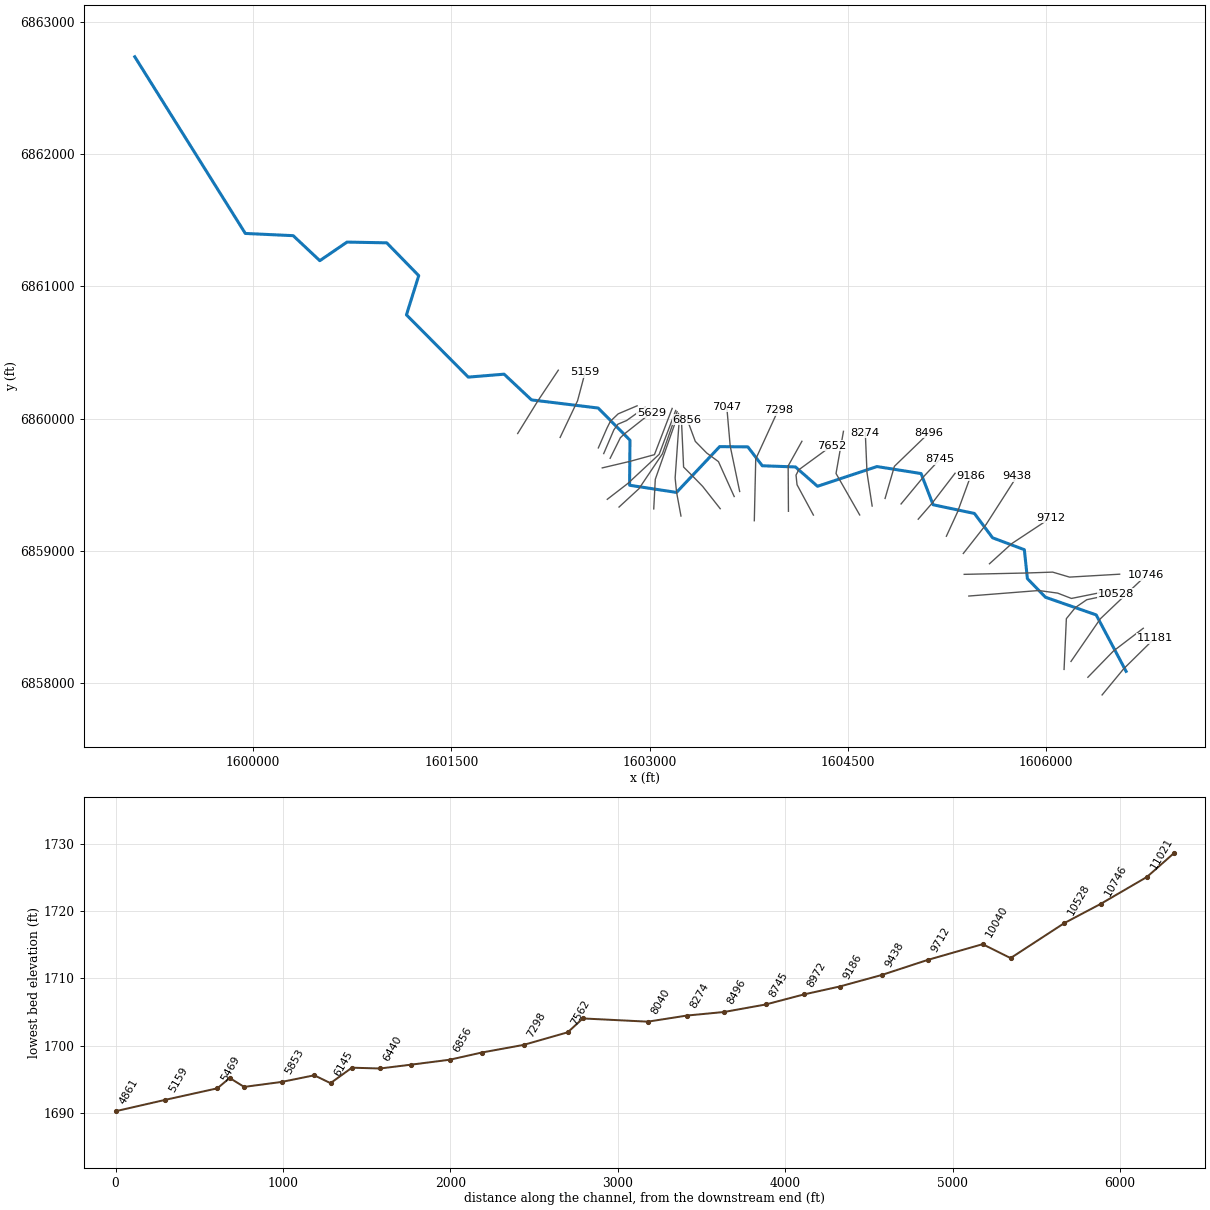
--- Elm 02 31.prj (project) ---

Proj Title=Elm 02 31 Base Level Engineering
Current Plan=p01
Default Exp/Contr=0.3,0.1
English Units
Geom File=g01
Flow File=f01
Plan File=p01
BEGIN DESCRIPTION:
Elm 02 31
END DESCRIPTION:

--- Elm 02 31.p01 (plan) ---

Plan Title=Multiple Run
Short Identifier=Multiple
Geom File=g01
Flow File=f01
Subcritical Flow
K Sum by GR= 0
Std Step Tol= 0.01
Critical Tol= 0.01
Num of Std Step Trials= 20
Max Error Tol= 0.3
Flow Tol Ratio= 0.001
Split Flow NTrial= 30
Split Flow Tol= 0.02
Split Flow Ratio= 0.02
Log Output Level= 0
Friction Slope Method= 1
Unsteady Friction Slope Method= 2
Unsteady Bridges Friction Slope Method= 1
Parabolic Critical Depth
Global Vel Dist=  1 , 1 , 1
Global Log Level= 0
CheckData=True
Encroach Param= -1, 0, 0, 0
BEGIN DESCRIPTION:
Multiple Run
END DESCRIPTION:

--- Elm 02 31.f01 (steady flow) ---

Flow Title=Multiple
Number of Profiles=7
Profile Names=10-year,25-year,50-year,1pct_min,100-year,1pct_plu,500-year
River Rch & RM= Elm 02 31,Reach-1,11181
     197     269     328     248     398     547     591
River Rch & RM= Elm 02 31,Reach-1,4223
     286     399     493     377     605     832     923
River Rch & RM= Elm 02 31,Reach-1,16
    2270    3400    4400    3500    5610    7720    9270
Boundary for River Rch & Prof#=Elm 02 31,Reach-1,1
Up Type=0
Dn Type=3
Dn Slope=0.001
Boundary for River Rch & Prof#=Elm 02 31,Reach-1,2
Up Type=0
Dn Type=3
Dn Slope=0.001
Boundary for River Rch & Prof#=Elm 02 31,Reach-1,3
Up Type=0
Dn Type=3
Dn Slope=0.001
Boundary for River Rch & Prof#=Elm 02 31,Reach-1,4
Up Type=0
Dn Type=3
Dn Slope=0.001
Boundary for River Rch & Prof#=Elm 02 31,Reach-1,5
Up Type=0
Dn Type=3
Dn Slope=0.001
Boundary for River Rch & Prof#=Elm 02 31,Reach-1,6
Up Type=0
Dn Type=3
Dn Slope=0.001
Boundary for River Rch & Prof#=Elm 02 31,Reach-1,7
Up Type=0
Dn Type=3
Dn Slope=0.001

--- Elm 02 31.g01 (geometry) ---

Geom Title=Existing Conditions

River Reach=Elm 02 31,Reach-1
Reach XY= 30
      1606605.00      6858088.00      1606378.57      6858515.14
      1605995.21      6858648.52      1605858.13      6858789.63
      1605835.25      6859008.42      1605594.90      6859098.39
      1605457.46      6859282.54      1605144.84      6859348.36
      1605053.75      6859584.49      1604720.22      6859637.48
      1604270.22      6859488.23      1604103.54      6859634.46
      1603852.53      6859643.46      1603743.17      6859786.38
      1603529.91      6859788.21      1603203.48      6859441.74
      1602848.57      6859496.02      1602851.55      6859836.75
      1602611.19      6860080.15      1602106.55      6860141.75
      1601899.15      6860336.46      1601628.13      6860314.16
      1601160.30      6860785.33      1601253.39      6861081.97
      1601011.19      6861330.19      1600710.86      6861335.94
      1600504.91      6861195.28      1600303.54      6861384.46
      1599941.33      6861401.23      1599105.00      6862738.00

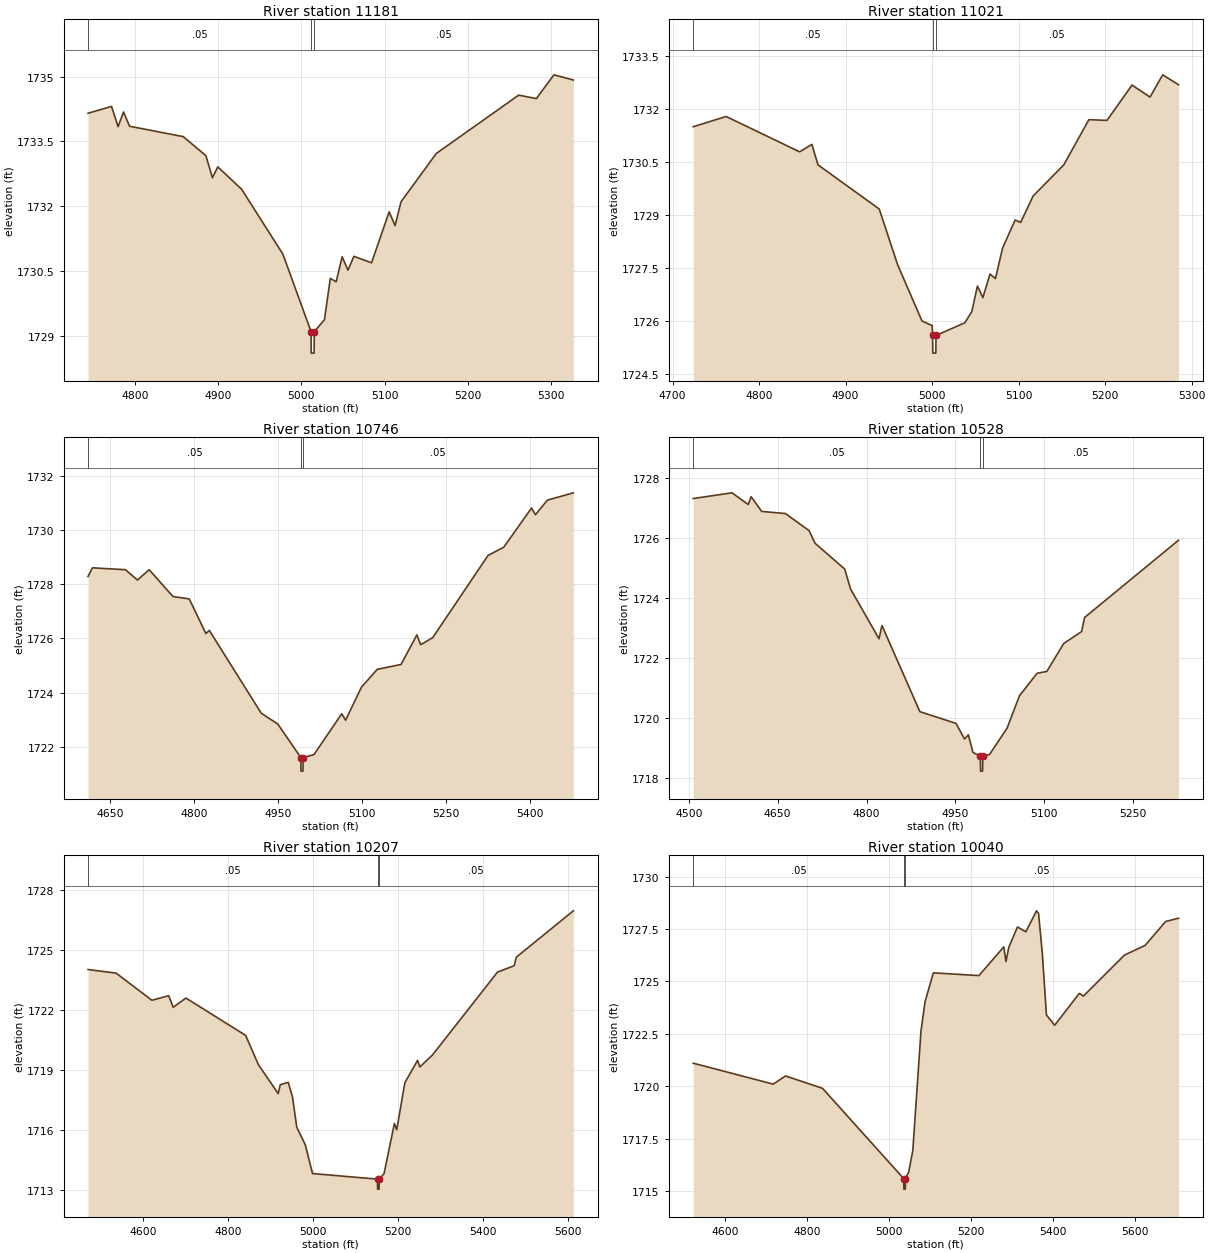
Type RM Length L Ch R = 1,11181,160,160,160
BEGIN DESCRIPTION:
Elm 02 31 10861.478
END DESCRIPTION:
XS GIS Cut Line= 3
      1606423.49      6857909.47      1606586.60      6858107.17
      1606819.34      6858336.58
#Sta/Elev= 30
  4743.7 1734.15  4771.9 1734.31  4779.8 1733.84  4786.3 1734.18  4793.6 1733.85
  4858.0 1733.61  4885.3 1733.17  4893.1 1732.66  4899.6 1732.91  4928.3 1732.39
  4977.8 1730.89  5011.6 1729.10  5011.8 1728.60  5015.3 1728.60  5015.6 1729.10
  5027.7 1729.37  5034.8 1730.33  5041.8 1730.25  5049.0 1730.83  5056.0 1730.52
  5063.1 1730.84  5084.3 1730.69  5105.5 1731.87  5112.6 1731.55  5119.7 1732.10
  5162.1 1733.22  5261.1 1734.57  5282.3 1734.49  5303.5 1735.04  5326.8 1734.92
#Mann=3,-1,0
  4743.7    0.05       0  5011.6    0.05       0  5015.6    0.05       0
Bank Sta=5011.6,5015.6
Exp/Cntr=0.3,0.1

Type RM Length L Ch R = 1,11021,275,275,275
BEGIN DESCRIPTION:
Elm 02 31 11021.09
END DESCRIPTION:
XS GIS Cut Line= 3
      1606315.85      6858043.16      1606508.58      6858241.09
      1606734.91      6858413.86
#Sta/Elev= 30
  4723.8 1731.50  4761.9 1731.79  4846.8 1730.79  4861.0 1731.00  4868.1 1730.42
  4938.9 1729.17  4960.0 1727.60  4988.3 1726.00  5000.1 1725.87  5000.5 1725.59
  5000.8 1725.09  5004.3 1725.09  5004.5 1725.59  5037.9 1725.95  5045.9 1726.27
  5052.4 1726.99  5058.7 1726.66  5066.9 1727.33  5073.2 1727.20  5081.5 1728.07
  5096.0 1728.86  5102.3 1728.79  5116.8 1729.54  5152.2 1730.42  5181.2 1731.70
  5202.1 1731.68  5231.1 1732.68  5251.9 1732.34  5266.5 1732.97  5284.8 1732.69
#Mann=3,-1,0
  4723.8    0.05       0  5000.5    0.03       0  5004.5    0.05       0
Bank Sta=5000.5,5004.5
Exp/Cntr=0.3,0.1

Type RM Length L Ch R = 1,10746,218,218,218
BEGIN DESCRIPTION:
Elm 02 31 10746.2
END DESCRIPTION:
XS GIS Cut Line= 3
      1606188.09      6858162.93      1606410.30      6858485.82
      1606755.25      6858813.44
#Sta/Elev= 30
  4609.9 1728.29  4617.7 1728.61  4676.8 1728.54  4698.2 1728.16  4719.2 1728.54
  4761.7 1727.55  4790.9 1727.46  4820.6 1726.18  4826.7 1726.30  4919.5 1723.24
  4949.1 1722.84  4990.4 1721.60  4990.6 1721.10  4994.1 1721.10  4994.4 1721.60
  5013.8 1721.71  5063.5 1723.22  5070.4 1722.98  5098.7 1724.20  5127.0 1724.86
  5169.5 1725.04  5197.8 1726.13  5204.7 1725.77  5226.1 1726.03  5325.2 1729.07
  5353.1 1729.37  5402.9 1730.82  5409.8 1730.57  5431.2 1731.11  5477.6 1731.38
#Mann=3,-1,0
  4609.9    0.05       0  4990.4    0.03       0  4994.4    0.05       0
Bank Sta=4990.4,4994.4
Exp/Cntr=0.3,0.1

Type RM Length L Ch R = 1,10528,321,321,321
BEGIN DESCRIPTION:
Elm 02 31 10527.92
END DESCRIPTION:
XS GIS Cut Line= 5
      1606135.70      6858102.49      1606153.06      6858486.61
      1606221.19      6858570.50      1606307.14      6858629.84
      1606524.58      6858675.97
#Sta/Elev= 30
  4507.4 1727.31  4573.0 1727.50  4600.3 1727.11  4605.3 1727.37  4623.0 1726.88
  4663.1 1726.81  4703.1 1726.24  4713.1 1725.82  4763.2 1724.96  4773.2 1724.29
  4821.1 1722.64  4826.1 1723.08  4890.1 1720.21  4951.1 1719.82  4965.5 1719.30
  4971.9 1719.44  4979.8 1718.85  4992.2 1718.73  4992.5 1718.23  4996.0 1718.23
  4996.2 1718.73  5007.5 1718.78  5037.3 1719.66  5058.2 1720.74  5088.0 1721.49
  5104.4 1721.55  5132.9 1722.48  5163.1 1722.88  5168.3 1723.35  5326.7 1725.92
#Mann=3,-1,0
  4507.4    0.05       0  4992.2    0.05       0  4996.2    0.05       0
Bank Sta=4992.2,4996.2
Exp/Cntr=0.3,0.1

Type RM Length L Ch R = 1,10207,167,167,167
BEGIN DESCRIPTION:
Elm 02 31 10207.31
END DESCRIPTION:
XS GIS Cut Line= 5
      1605415.18      6858657.74      1605943.85      6858699.41
      1606087.08      6858679.87      1606191.24      6858639.51
      1606540.06      6858709.79
#Sta/Elev= 30
  4469.8 1724.02  4535.8 1723.84  4620.1 1722.48  4659.6 1722.71  4670.2 1722.13
  4700.3 1722.59  4840.8 1720.72  4870.9 1719.25  4917.3 1717.81  4922.3 1718.25
  4941.1 1718.37  4951.1 1717.63  4961.1 1716.12  4981.2 1715.24  4998.2 1713.80
  5151.2 1713.52  5151.4 1713.02  5154.9 1713.02  5155.2 1713.52  5166.5 1713.79
  5191.0 1716.31  5196.4 1715.99  5215.6 1718.35  5245.5 1719.47  5250.9 1719.14
  5280.6 1719.74  5433.6 1723.89  5472.9 1724.21  5478.0 1724.64  5612.2 1726.96
#Mann=3,-1,0
  4469.8    0.05       0  5151.2    0.05       0  5155.2    0.05       0
Bank Sta=5151.2,5155.2
Exp/Cntr=0.3,0.1

Type RM Length L Ch R = 1,10040,328,328,328
BEGIN DESCRIPTION:
Elm 02 31 10039.61
END DESCRIPTION:
XS GIS Cut Line= 5
      1605380.02      6858821.80      1605856.61      6858832.22
      1606049.32      6858838.73      1606176.92      6858800.97
      1606556.29      6858823.05
#Sta/Elev= 30
  4522.9 1721.10  4717.9 1720.10  4747.9 1720.49  4838.0 1719.90  5036.0 1715.59
  5036.3 1715.09  5039.8 1715.09  5040.0 1715.59  5048.0 1715.90  5058.0 1716.92
  5078.0 1722.63  5088.0 1724.04  5108.1 1725.41  5219.2 1725.28  5279.8 1726.65
  5285.0 1725.95  5292.2 1726.64  5313.1 1727.60  5333.6 1727.37  5359.5 1728.37
  5364.5 1728.25  5373.7 1726.34  5383.7 1723.40  5403.7 1722.91  5463.8 1724.43
  5473.8 1724.30  5574.0 1726.26  5624.1 1726.72  5674.2 1727.86  5705.5 1728.02
#Mann=3,-1,0
  4522.9    0.05       0  5036.0    0.03       0  5040.0    0.05       0
Bank Sta=5036,5040
Exp/Cntr=0.3,0.1

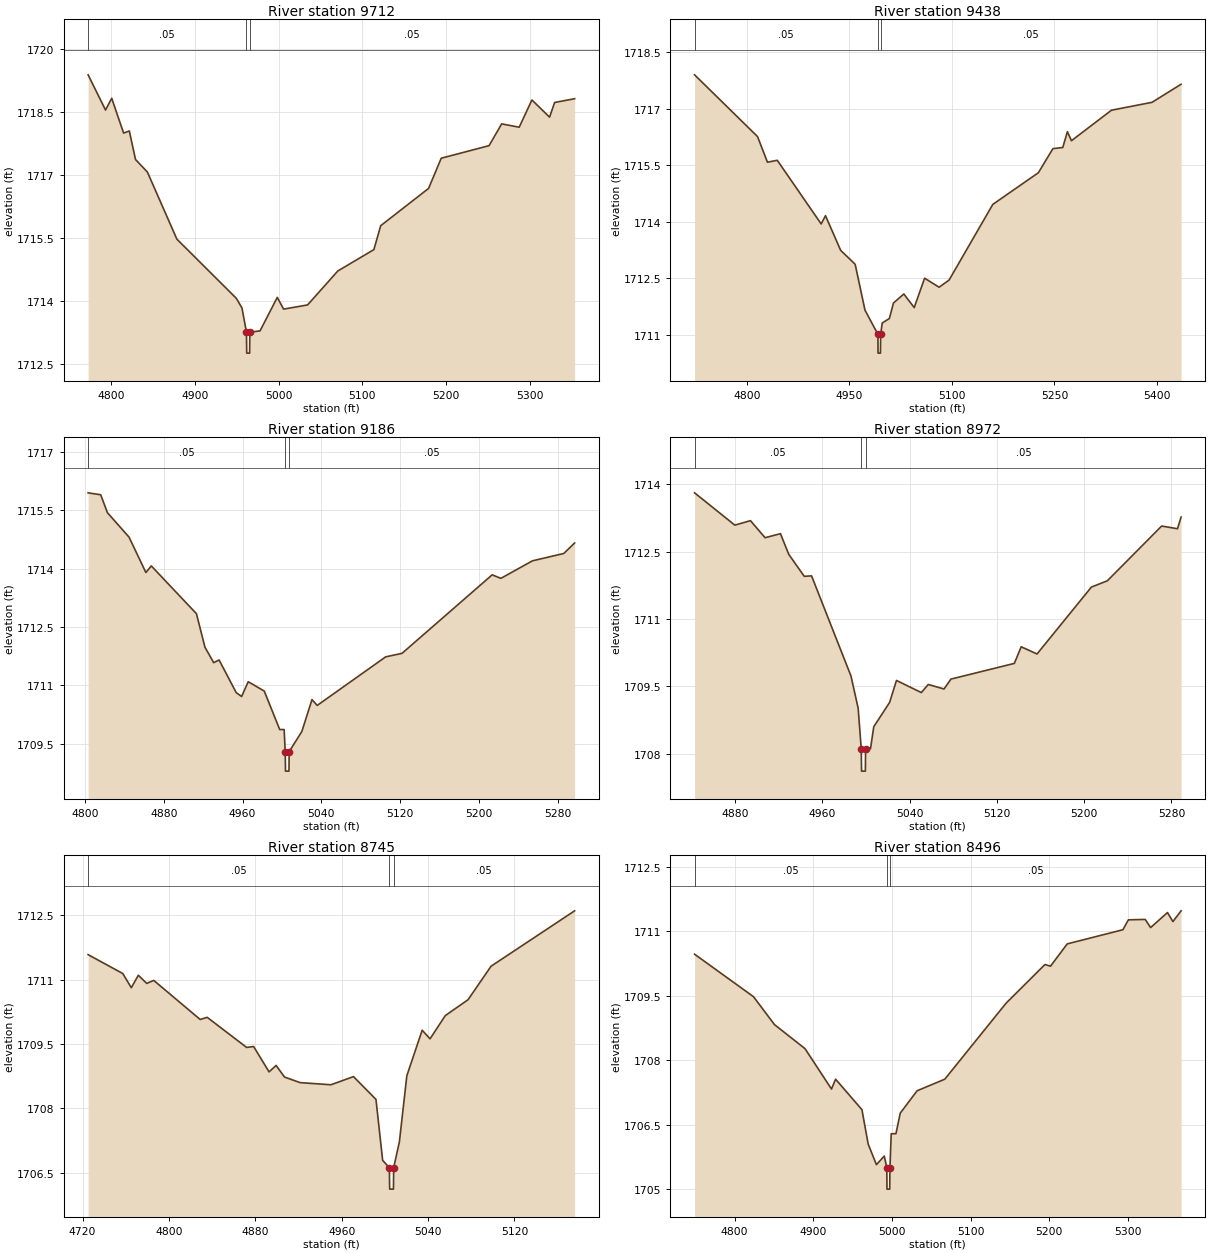
Type RM Length L Ch R = 1,9712,274,274,274
BEGIN DESCRIPTION:
Elm 02 31 9711.68
END DESCRIPTION:
XS GIS Cut Line= 3
      1605571.45      6858901.88      1605739.42      6859054.22
      1606034.96      6859249.51
#Sta/Elev= 30
  4772.6 1719.39  4793.4 1718.55  4800.8 1718.83  4815.0 1718.00  4821.8 1718.05
  4829.2 1717.37  4843.4 1717.07  4878.6 1715.47  4949.5 1714.06  4956.3 1713.83
  4961.7 1713.25  4962.0 1712.75  4965.5 1712.75  4965.7 1713.25  4977.9 1713.28
  4998.5 1714.08  5006.1 1713.80  5034.7 1713.90  5070.8 1714.71  5113.9 1715.22
  5122.0 1715.79  5179.2 1716.68  5194.3 1717.40  5251.4 1717.70  5266.5 1718.22
  5287.4 1718.14  5302.6 1718.79  5323.7 1718.38  5329.7 1718.73  5353.6 1718.82
#Mann=3,-1,0
  4772.6    0.05       0  4961.7    0.03       0  4965.7    0.05       0
Bank Sta=4961.7,4965.7
Exp/Cntr=0.3,0.1

Type RM Length L Ch R = 1,9438,252,252,252
BEGIN DESCRIPTION:
Elm 02 31 9438.29
END DESCRIPTION:
XS GIS Cut Line= 3
      1605373.53      6858980.00      1605545.41      6859198.75
      1605779.24      6859563.79
#Sta/Elev= 30
  4723.5 1717.90  4815.6 1716.26  4830.1 1715.58  4844.5 1715.63  4908.7 1713.94
  4915.0 1714.16  4937.2 1713.24  4958.4 1712.87  4972.8 1711.65  4991.7 1711.01
  4991.9 1710.51  4995.4 1710.51  4995.7 1711.01  4998.0 1711.31  5008.5 1711.43
  5014.4 1711.84  5029.6 1712.08  5044.8 1711.72  5060.0 1712.50  5081.2 1712.26
  5095.8 1712.45  5159.8 1714.46  5226.4 1715.30  5247.7 1715.94  5262.1 1715.97
  5268.9 1716.39  5274.8 1716.15  5333.3 1716.96  5392.7 1717.17  5435.2 1717.65
#Mann=3,-1,0
  4723.5    0.05       0  4991.7    0.03       0  4995.7    0.05       0
Bank Sta=4991.7,4995.7
Exp/Cntr=0.3,0.1

Type RM Length L Ch R = 1,9186,214,214,214
BEGIN DESCRIPTION:
Elm 02 31 9186.07
END DESCRIPTION:
XS GIS Cut Line= 3
      1605245.23      6859110.19      1605328.56      6859291.16
      1605430.05      6859568.32
#Sta/Elev= 30
  4803.0 1715.95  4815.8 1715.90  4822.6 1715.44  4844.6 1714.81  4861.7 1713.90
  4867.2 1714.07  4913.1 1712.84  4921.7 1711.98  4930.6 1711.58  4936.1 1711.65
  4953.5 1710.81  4959.0 1710.71  4965.7 1711.09  4982.0 1710.85  4997.7 1709.86
  5002.2 1709.86  5003.3 1709.29  5003.6 1708.79  5007.1 1708.79  5007.3 1709.29
  5020.2 1709.81  5030.5 1710.63  5035.8 1710.48  5105.4 1711.73  5122.0 1711.82
  5213.6 1713.84  5222.5 1713.75  5254.5 1714.20  5286.4 1714.39  5297.4 1714.66
#Mann=3,-1,0
  4803.0    0.05       0  5003.3    0.03       0  5007.3    0.05       0
Bank Sta=5003.3,5007.3
Exp/Cntr=0.3,0.1

Type RM Length L Ch R = 1,8972,227,227,227
BEGIN DESCRIPTION:
Elm 02 31 8972.16
END DESCRIPTION:
XS GIS Cut Line= 3
      1605032.22      6859239.22      1605136.35      6859358.98
      1605311.09      6859586.78
#Sta/Elev= 30
  4843.0 1713.81  4879.9 1713.09  4894.2 1713.19  4907.6 1712.81  4921.7 1712.90
  4929.3 1712.44  4943.5 1711.95  4950.2 1711.96  4986.3 1709.73  4992.9 1709.01
  4995.7 1708.11  4996.0 1707.61  4999.5 1707.61  4999.7 1708.11  5004.2 1708.11
  5007.2 1708.60  5021.7 1709.14  5028.0 1709.63  5050.8 1709.36  5057.1 1709.54
  5071.6 1709.44  5077.9 1709.66  5136.0 1710.01  5142.3 1710.38  5156.8 1710.22
  5206.6 1711.71  5221.2 1711.85  5271.0 1713.07  5285.5 1713.01  5288.8 1713.27
#Mann=3,-1,0
  4843.0    0.05       0  4995.7    0.03       0  4999.7    0.05       0
Bank Sta=4995.7,4999.7
Exp/Cntr=0.3,0.1

Type RM Length L Ch R = 1,8745,249,249,249
BEGIN DESCRIPTION:
Elm 02 31 8744.5
END DESCRIPTION:
XS GIS Cut Line= 3
      1604902.53      6859354.60      1605077.91      6859566.44
      1605198.14      6859694.41
#Sta/Elev= 30
  4725.2 1711.58  4757.3 1711.14  4765.2 1710.81  4771.7 1711.10  4779.5 1710.91
  4786.0 1710.98  4829.0 1710.07  4835.5 1710.12  4872.0 1709.42  4878.5 1709.44
  4892.8 1708.85  4899.3 1709.00  4907.1 1708.73  4921.5 1708.60  4950.1 1708.55
  4971.0 1708.74  4991.8 1708.21  4998.0 1706.79  5004.2 1706.62  5004.5 1706.12
  5008.0 1706.12  5008.2 1706.62  5013.5 1707.22  5020.4 1708.76  5034.6 1709.82
  5041.9 1709.62  5056.0 1710.16  5077.1 1710.53  5098.4 1711.31  5175.8 1712.60
#Mann=3,-1,0
  4725.2    0.05       0  5004.2    0.03       0  5008.2    0.05       0
Bank Sta=5004.2,5008.2
Exp/Cntr=0.3,0.1

Type RM Length L Ch R = 1,8496,222,222,222
BEGIN DESCRIPTION:
Elm 02 31 8496.14
END DESCRIPTION:
XS GIS Cut Line= 3
      1604781.47      6859396.09      1604851.99      6859639.14
      1605114.55      6859893.02
#Sta/Elev= 30
  4749.2 1710.47  4824.1 1709.48  4850.8 1708.83  4889.6 1708.27  4923.2 1707.33
  4928.4 1707.56  4961.9 1706.85  4969.8 1706.05  4980.3 1705.57  4990.3 1705.77
  4993.5 1705.50  4993.7 1705.00  4997.2 1705.00  4997.5 1705.50  4999.1 1706.29
  5005.1 1706.29  5010.6 1706.77  5032.0 1707.29  5067.2 1707.56  5145.1 1709.33
  5194.5 1710.23  5201.5 1710.19  5222.8 1710.71  5293.6 1711.04  5300.5 1711.27
  5321.9 1711.28  5328.8 1711.09  5350.2 1711.44  5357.1 1711.23  5367.5 1711.48
#Mann=3,-1,0
  4749.2    0.05       0  4993.5    0.03       0  4997.5    0.05       0
Bank Sta=4993.5,4997.5
Exp/Cntr=0.3,0.1

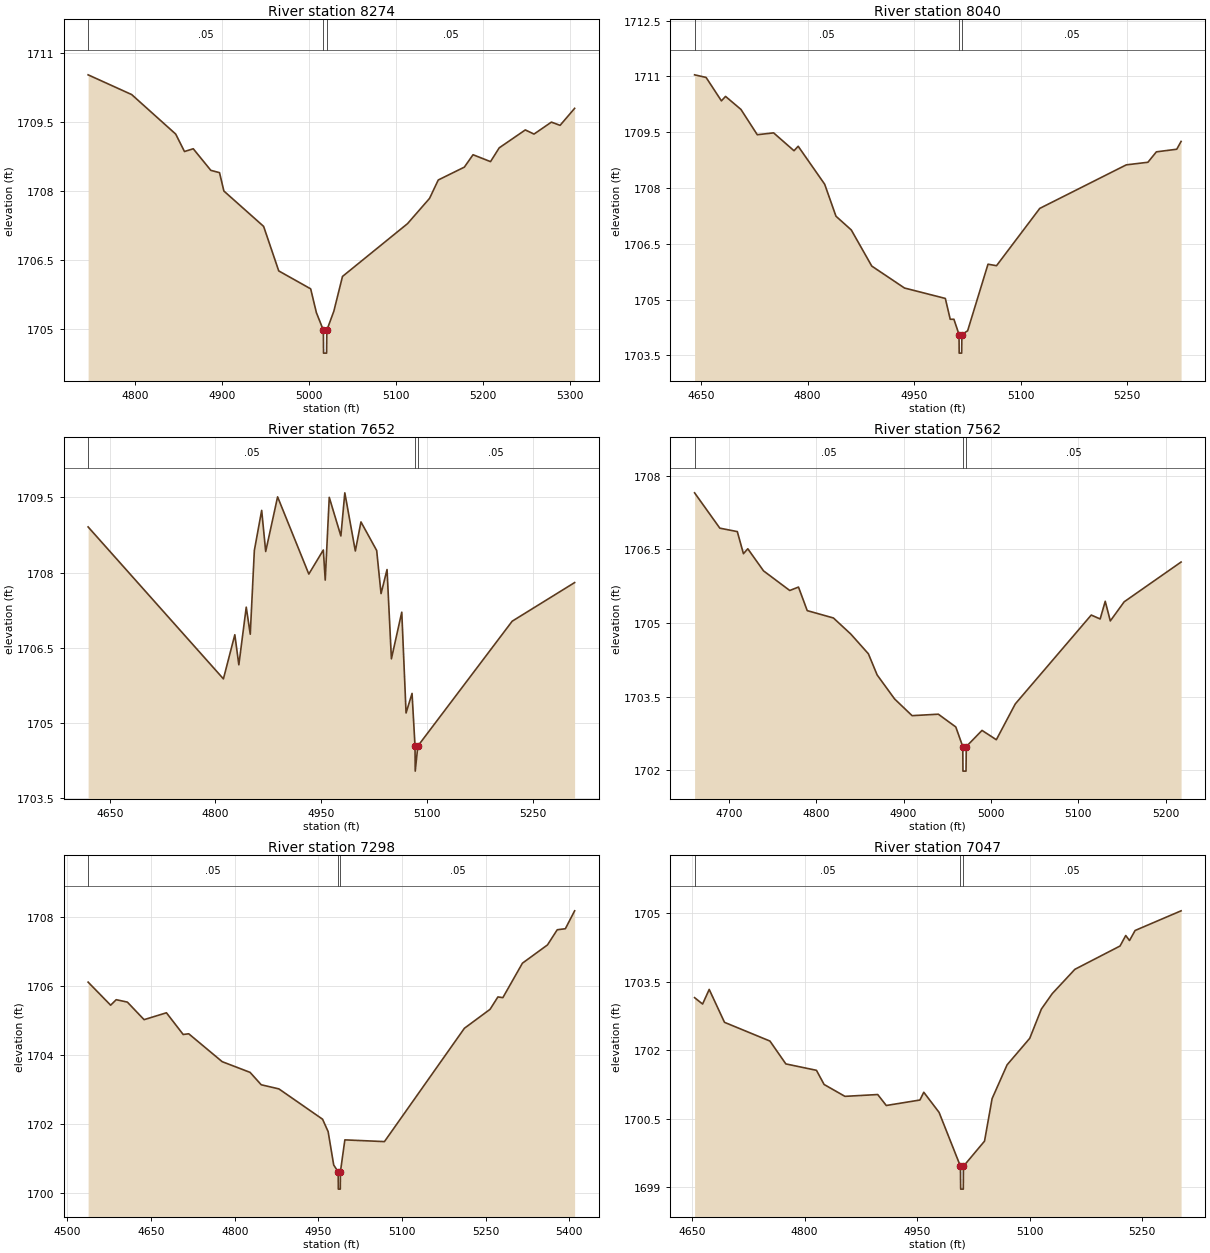
Type RM Length L Ch R = 1,8274,234,234,234
BEGIN DESCRIPTION:
Elm 02 31 8274.24
END DESCRIPTION:
XS GIS Cut Line= 3
      1604683.82      6859338.53      1604644.75      6859591.40
      1604631.80      6859894.65
#Sta/Elev= 30
  4746.1 1710.53  4796.2 1710.10  4846.8 1709.24  4856.9 1708.86  4867.0 1708.92
  4887.2 1708.45  4897.2 1708.40  4902.2 1708.00  4947.9 1707.23  4965.3 1706.26
  5002.0 1705.87  5008.6 1705.35  5016.6 1704.97  5016.8 1704.47  5020.3 1704.47
  5020.6 1704.97  5028.6 1705.38  5038.6 1706.14  5113.4 1707.29  5138.7 1707.84
  5148.7 1708.24  5178.7 1708.52  5188.7 1708.79  5208.8 1708.64  5218.8 1708.94
  5248.8 1709.33  5258.8 1709.24  5278.8 1709.50  5288.8 1709.43  5305.5 1709.80
#Mann=3,-1,0
  4746.1    0.05       0  5016.6    0.03       0  5020.6    0.05       0
Bank Sta=5016.6,5020.6
Exp/Cntr=0.3,0.1

Type RM Length L Ch R = 1,8040,388,388,388
BEGIN DESCRIPTION:
Elm 02 31 8039.62
END DESCRIPTION:
XS GIS Cut Line= 3
      1604589.40      6859271.32      1604410.37      6859584.89
      1604466.62      6859903.99
#Sta/Elev= 30
  4640.8 1711.04  4657.0 1710.97  4678.6 1710.34  4684.4 1710.46  4706.1 1710.11
  4729.1 1709.43  4752.1 1709.48  4780.8 1709.00  4786.7 1709.12  4824.0 1708.10
  4839.9 1707.24  4861.5 1706.87  4890.3 1705.90  4936.4 1705.31  4993.9 1705.03
  5000.8 1704.47  5006.0 1704.47  5013.2 1704.06  5013.4 1703.56  5016.9 1703.56
  5017.2 1704.06  5025.3 1704.16  5054.0 1705.95  5066.0 1705.91  5126.9 1707.45
  5248.7 1708.62  5279.2 1708.69  5291.1 1708.97  5319.8 1709.04  5325.9 1709.25
#Mann=3,-1,0
  4640.8    0.05       0  5013.2    0.03       0  5017.2    0.05       0
Bank Sta=5013.2,5017.2
Exp/Cntr=0.3,0.1

Type RM Length L Ch R = 1,7652,90,90,90
BEGIN DESCRIPTION:
Elm 02 31 7651.55
END DESCRIPTION:
XS GIS Cut Line= 5
      1604239.22      6859270.43      1604115.52      6859499.60
      1604107.71      6859572.52      1604128.54      6859612.88
      1604379.84      6859796.47
#Sta/Elev= 30
  4619.3 1708.91  4811.3 1705.88  4827.5 1706.76  4833.2 1706.16  4843.7 1707.31
  4849.4 1706.77  4855.2 1708.44  4865.6 1709.24  4871.3 1708.42  4888.2 1709.51
  4932.5 1707.97  4953.1 1708.45  4955.8 1707.85  4961.5 1709.50  4978.0 1708.73
  4983.6 1709.59  4998.5 1708.43  5006.5 1709.01  5028.8 1708.44  5035.0 1707.58
  5043.5 1708.06  5049.7 1706.28  5064.4 1707.21  5070.5 1705.20  5079.0 1705.59
  5083.2 1704.54  5083.5 1704.04  5087.2 1704.54  5221.1 1707.03  5309.7 1707.80
#Mann=3,-1,0
  4619.3    0.05       0  5083.2    0.03       0  5087.2    0.05       0
Bank Sta=5083.2,5087.2
Exp/Cntr=0.3,0.1

Type RM Length L Ch R = 1,7562,264,264,264
BEGIN DESCRIPTION:
Elm 02 31 7562.49
END DESCRIPTION:
XS GIS Cut Line= 3
      1604050.37      6859299.14      1604048.20      6859642.06
      1604152.38      6859828.72
#Sta/Elev= 30
  4660.8 1707.65  4689.7 1706.93  4709.7 1706.86  4716.7 1706.41  4721.7 1706.51
  4739.7 1706.06  4769.7 1705.66  4779.7 1705.73  4789.7 1705.25  4819.7 1705.10
  4839.7 1704.77  4859.7 1704.37  4869.7 1703.94  4889.7 1703.45  4909.7 1703.11
  4939.7 1703.14  4959.7 1702.88  4967.7 1702.48  4967.9 1701.98  4971.4 1701.98
  4971.7 1702.48  4989.7 1702.81  5006.1 1702.62  5027.8 1703.35  5114.7 1705.16
  5124.9 1705.08  5130.7 1705.44  5136.5 1705.04  5152.4 1705.43  5217.5 1706.24
#Mann=3,-1,0
  4660.8    0.05       0  4967.7    0.03       0  4971.7    0.05       0
Bank Sta=4967.7,4971.7
Exp/Cntr=0.3,0.1

Type RM Length L Ch R = 1,7298,251,251,251
BEGIN DESCRIPTION:
Elm 02 31 7297.8
END DESCRIPTION:
XS GIS Cut Line= 3
      1603792.12      6859227.58      1603802.97      6859694.14
      1603972.25      6860063.07
#Sta/Elev= 30
  4537.1 1706.11  4577.5 1705.44  4587.5 1705.60  4607.5 1705.53  4637.5 1705.02
  4677.6 1705.22  4707.6 1704.59  4717.6 1704.61  4777.6 1703.80  4827.6 1703.49
  4847.6 1703.13  4879.3 1703.01  4957.6 1702.13  4967.6 1701.77  4977.6 1700.80
  4985.6 1700.60  4985.9 1700.10  4989.4 1700.10  4989.6 1700.60  4997.6 1701.53
  5068.6 1701.48  5212.0 1704.77  5258.0 1705.32  5272.1 1705.68  5281.0 1705.66
  5316.1 1706.66  5361.0 1707.19  5378.5 1707.63  5393.1 1707.66  5409.7 1708.18
#Mann=3,-1,0
  4537.1    0.05       0  4985.6    0.05       0  4989.6    0.05       0
Bank Sta=4985.6,4989.6
Exp/Cntr=0.3,0.1

Type RM Length L Ch R = 1,7047,191,191,191
BEGIN DESCRIPTION:
Elm 02 31 7047.42
END DESCRIPTION:
XS GIS Cut Line= 3
      1603681.44      6859448.92      1603609.83      6859791.80
      1603583.79      6860089.08
#Sta/Elev= 30
  4653.2 1703.15  4663.9 1703.01  4672.7 1703.33  4693.1 1702.61  4753.7 1702.20
  4774.9 1701.70  4815.7 1701.56  4825.9 1701.25  4853.7 1700.99  4897.4 1701.03
  4908.8 1700.79  4953.7 1700.91  4958.8 1701.08  4979.2 1700.64  5007.7 1699.46
  5008.0 1698.96  5011.5 1698.96  5011.7 1699.46  5039.8 1700.01  5049.9 1700.94
  5069.9 1701.68  5100.1 1702.26  5115.6 1702.90  5130.2 1703.24  5160.3 1703.77
  5220.5 1704.28  5228.1 1704.51  5233.1 1704.40  5240.6 1704.62  5301.9 1705.05
#Mann=3,-1,0
  4653.2    0.05       0  5007.7    0.03       0  5011.7    0.05       0
Bank Sta=5007.7,5011.7
Exp/Cntr=0.3,0.1

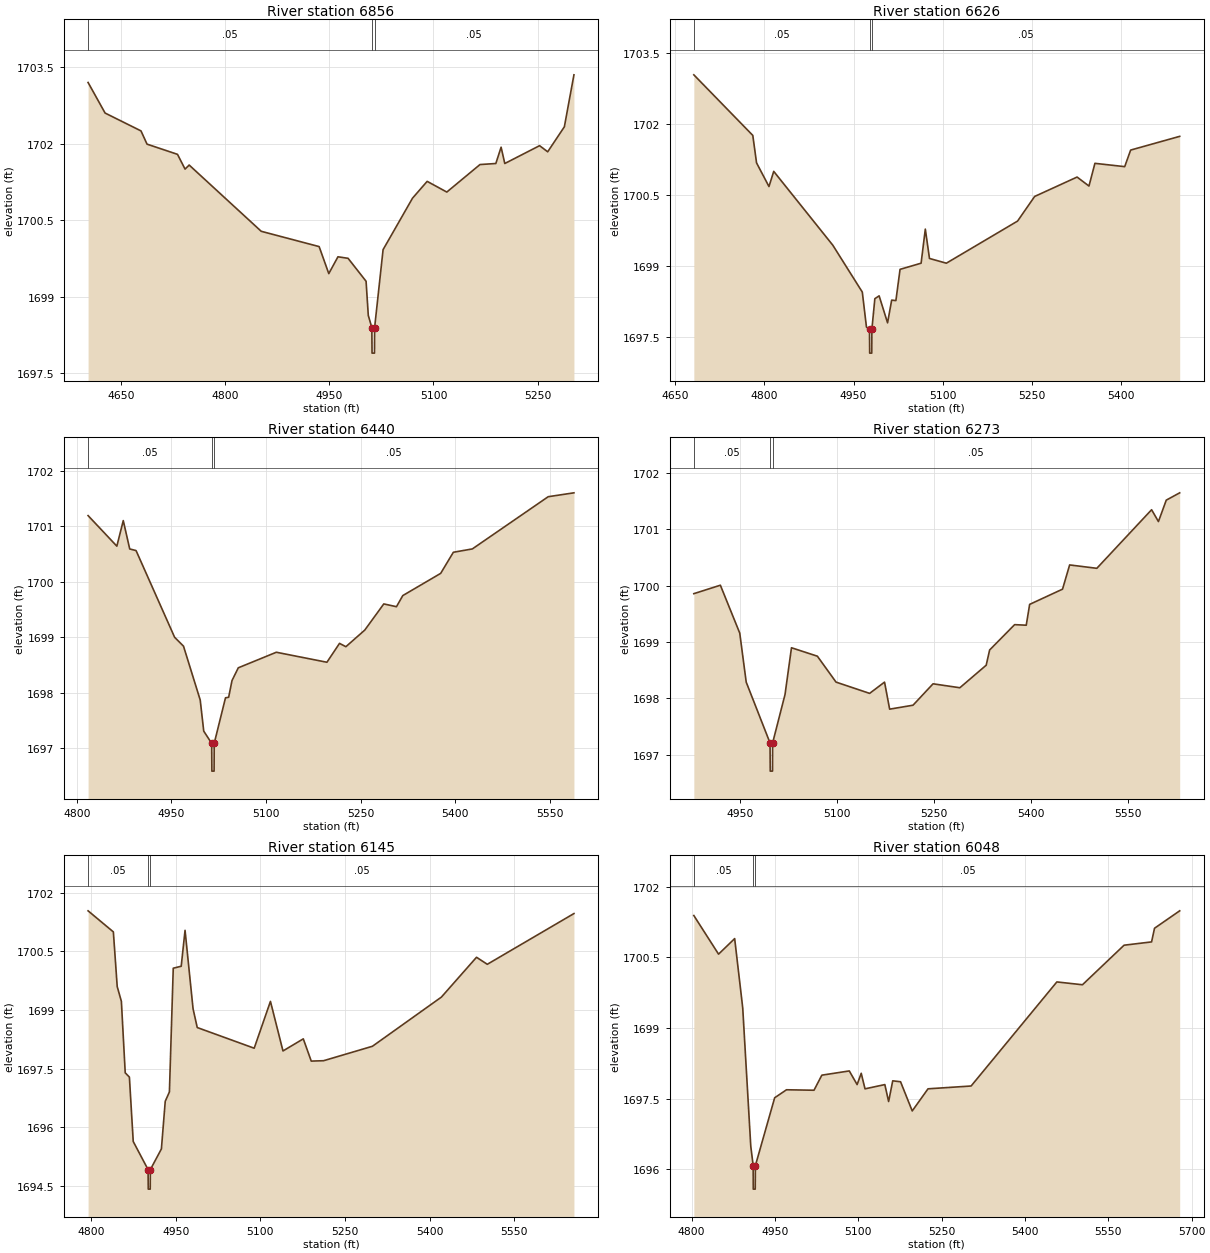
Type RM Length L Ch R = 1,6856,230,230,230
BEGIN DESCRIPTION:
Elm 02 31 6855.72
END DESCRIPTION:
XS GIS Cut Line= 5
      1603640.06      6859410.62      1603520.89      6859674.78
      1603431.73      6859740.17      1603345.66      6859828.09
      1603284.33      6859993.49
#Sta/Elev= 30
  4602.5 1703.20  4627.0 1702.60  4678.7 1702.25  4687.4 1701.99  4731.3 1701.79
  4742.2 1701.50  4748.1 1701.58  4851.9 1700.28  4935.3 1699.98  4949.2 1699.45
  4962.4 1699.78  4977.0 1699.75  5002.9 1699.30  5006.1 1698.63  5011.2 1698.39
  5011.5 1697.89  5015.0 1697.89  5015.2 1698.39  5027.4 1699.92  5069.8 1700.93
  5090.9 1701.26  5119.2 1701.05  5167.0 1701.59  5189.8 1701.61  5197.4 1701.93
  5202.7 1701.61  5252.8 1701.96  5264.5 1701.84  5288.5 1702.33  5302.3 1703.35
#Mann=3,-1,0
  4602.5    0.05       0  5011.2    0.03       0  5015.2    0.05       0
Bank Sta=5011.2,5015.2
Exp/Cntr=0.3,0.1

Type RM Length L Ch R = 1,6626,186,186,186
BEGIN DESCRIPTION:
Elm 02 31 6626.42
END DESCRIPTION:
XS GIS Cut Line= 5
      1603534.14      6859318.64      1603401.12      6859487.78
      1603327.57      6859563.30      1603257.18      6859633.69
      1603239.00      6860030.43
#Sta/Elev= 30
  4681.4 1703.04  4780.6 1701.76  4786.9 1701.18  4807.8 1700.68  4815.8 1701.00
  4915.2 1699.44  4964.8 1698.45  4971.8 1697.71  4976.9 1697.66  4977.2 1697.16
  4980.7 1697.16  4980.9 1697.66  4985.9 1698.31  4993.1 1698.37  5007.3 1697.80
  5014.2 1698.28  5021.3 1698.27  5028.3 1698.93  5063.7 1699.06  5070.8 1699.78
  5077.8 1699.16  5106.2 1699.06  5226.0 1699.95  5254.7 1700.47  5326.1 1700.88
  5346.1 1700.69  5356.1 1701.17  5406.2 1701.10  5416.2 1701.45  5498.7 1701.74
#Mann=3,-1,0
  4681.4    0.05       0  4976.9    0.03       0  4980.9    0.05       0
Bank Sta=4976.9,4980.9
Exp/Cntr=0.3,0.1

Type RM Length L Ch R = 1,6440,167,167,167
BEGIN DESCRIPTION:
Elm 02 31 6439.51
END DESCRIPTION:
XS GIS Cut Line= 4
      1603237.26      6859263.13      1603203.87      6859443.94
      1603193.14      6859551.21      1603226.85      6860028.75
#Sta/Elev= 30
  4817.8 1701.19  4863.4 1700.64  4873.6 1701.10  4883.8 1700.59  4893.9 1700.56
  4955.0 1699.00  4969.1 1698.84  4995.6 1697.87  5001.2 1697.31  5013.8 1697.09
  5014.1 1696.59  5017.6 1696.59  5017.8 1697.09  5035.7 1697.91  5040.7 1697.92
  5046.0 1698.22  5056.0 1698.45  5116.3 1698.73  5196.5 1698.55  5216.5 1698.89
  5226.6 1698.83  5256.6 1699.13  5286.7 1699.60  5306.8 1699.55  5316.8 1699.75
  5376.9 1700.15  5397.0 1700.53  5427.1 1700.59  5547.4 1701.53  5588.2 1701.60
#Mann=3,-1,0
  4817.8    0.05       0  5013.8    0.03       0  5017.8    0.05       0
Bank Sta=5013.8,5017.8
Exp/Cntr=0.3,0.1

Type RM Length L Ch R = 1,6273,128,128,128
BEGIN DESCRIPTION:
Elm 02 31 6272.59
END DESCRIPTION:
XS GIS Cut Line= 4
      1603031.34      6859316.99      1603037.85      6859440.69
      1603042.94      6859540.77      1603218.15      6860039.08
#Sta/Elev= 30
  4878.2 1699.86  4919.3 1700.01  4949.3 1699.16  4959.3 1698.29  4996.2 1697.21
  4996.5 1696.71  5000.0 1696.71  5000.2 1697.21  5019.4 1698.07  5029.4 1698.90
  5069.5 1698.75  5098.4 1698.29  5150.4 1698.09  5173.5 1698.29  5181.4 1697.81
  5217.6 1697.88  5248.6 1698.26  5290.1 1698.19  5330.9 1698.59  5336.2 1698.86
  5374.9 1699.31  5392.9 1699.30  5398.2 1699.67  5449.1 1699.94  5460.1 1700.37
  5502.2 1700.31  5587.0 1701.35  5597.6 1701.14  5609.7 1701.52  5630.5 1701.65
#Mann=3,-1,0
  4878.2    0.05       0  4996.2    0.03       0  5000.2    0.05       0
Bank Sta=4996.2,5000.2
Exp/Cntr=0.3,0.1

Type RM Length L Ch R = 1,6145,97,97,97
BEGIN DESCRIPTION:
Elm 02 31 6144.54
END DESCRIPTION:
XS GIS Cut Line= 4
      1602768.73      6859331.07      1602919.58      6859469.99
      1603096.64      6859733.57      1603207.74      6860052.99
#Sta/Elev= 30
  4794.7 1701.54  4839.5 1701.00  4846.3 1699.60  4853.7 1699.22  4860.5 1697.39
  4867.9 1697.28  4874.7 1695.63  4901.0 1694.91  4901.3 1694.41  4904.8 1694.41
  4905.0 1694.91  4924.6 1695.44  4931.4 1696.66  4938.8 1696.90  4945.6 1700.07
  4959.7 1700.12  4966.5 1701.04  4980.7 1699.03  4988.1 1698.55  5089.0 1698.02
  5117.8 1699.22  5140.0 1697.95  5176.0 1698.26  5190.1 1697.69  5212.0 1697.70
  5298.5 1698.07  5420.7 1699.33  5482.9 1700.35  5502.0 1700.17  5655.5 1701.47
#Mann=3,-1,0
  4794.7    0.05       0  4901.0    0.03       0  4905.0    0.05       0
Bank Sta=4901,4905
Exp/Cntr=0.3,0.1

Type RM Length L Ch R = 1,6048,195,195,195
BEGIN DESCRIPTION:
Elm 02 31 6047.76
END DESCRIPTION:
XS GIS Cut Line= 4
      1602679.79      6859389.70      1602836.03      6859510.13
      1603072.33      6859730.10      1603197.34      6860061.71
#Sta/Elev= 30
  4804.0 1701.39  4848.5 1700.57  4877.5 1700.90  4892.0 1699.43  4906.5 1696.49
  4910.8 1696.08  4911.0 1695.58  4914.5 1695.58  4914.8 1696.08  4949.5 1697.52
  4970.8 1697.69  5020.3 1697.68  5034.4 1698.00  5083.8 1698.09  5097.9 1697.80
  5105.3 1698.04  5112.1 1697.71  5147.8 1697.80  5154.6 1697.44  5162.0 1697.88
  5176.1 1697.86  5197.1 1697.24  5225.5 1697.71  5303.1 1697.77  5457.4 1699.98
  5503.5 1699.92  5578.4 1700.76  5627.9 1700.83  5633.2 1701.12  5678.5 1701.49
#Mann=3,-1,0
  4804.0    0.05       0  4910.8    0.05       0  4914.8    0.05       0
Bank Sta=4910.8,4914.8
Exp/Cntr=0.3,0.1

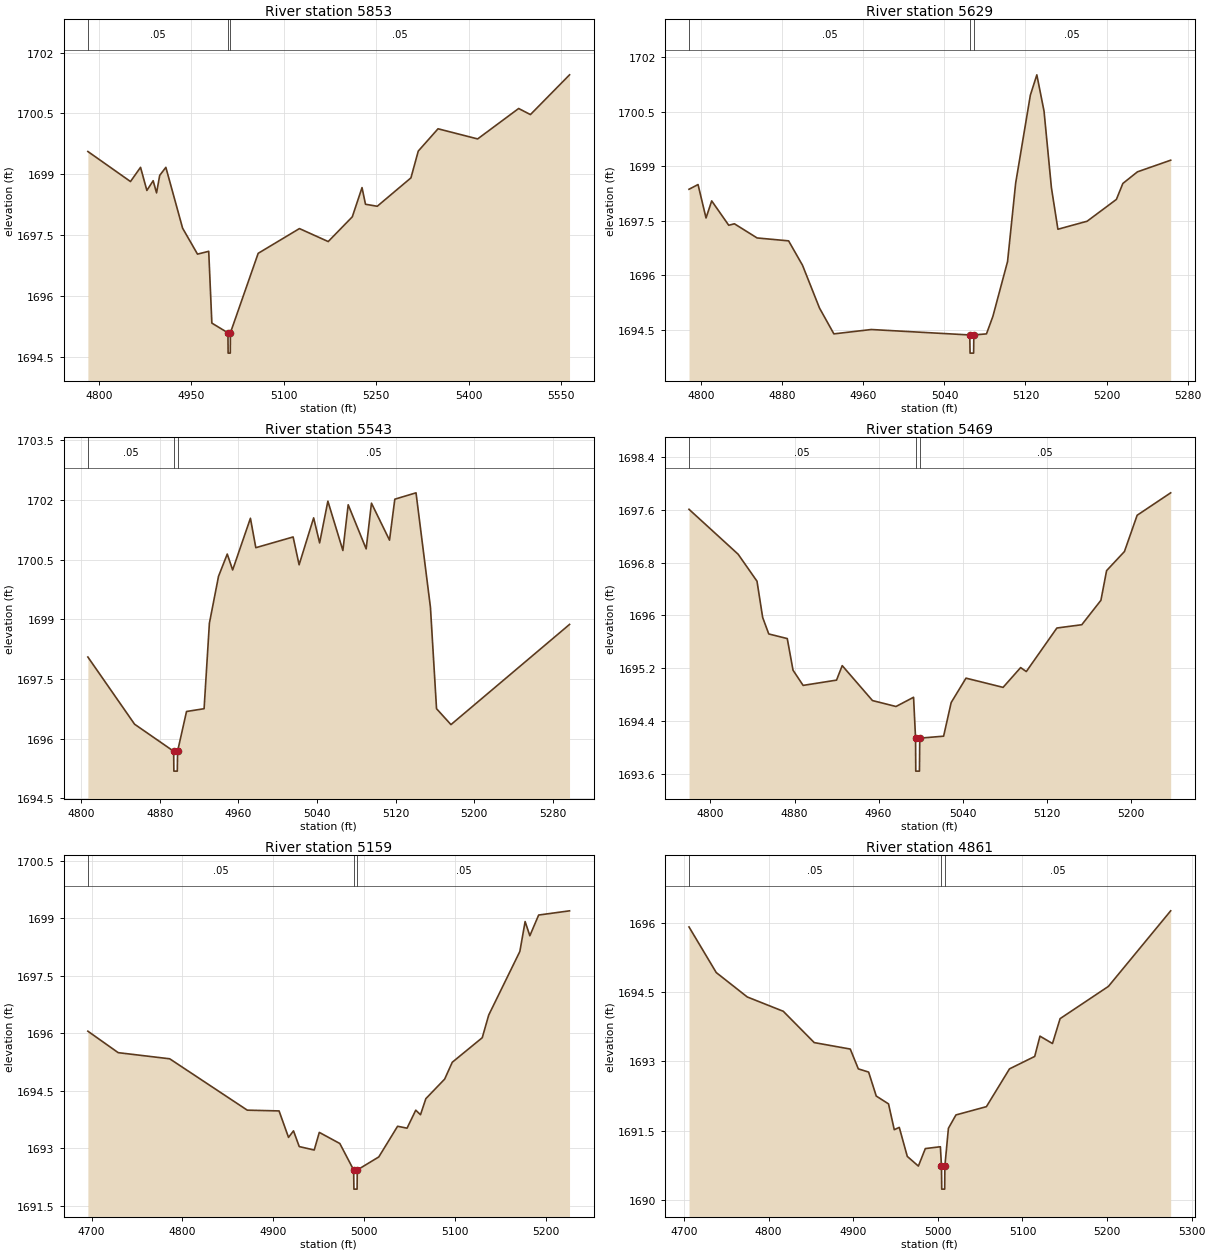
Type RM Length L Ch R = 1,5853,224,224,224
BEGIN DESCRIPTION:
Elm 02 31 5853.07
END DESCRIPTION:
XS GIS Cut Line= 4
      1602641.80      6859627.32      1602853.39      6859677.23
      1603036.59      6859727.51      1603170.63      6860077.34
#Sta/Elev= 30
  4781.9 1699.56  4851.1 1698.82  4867.4 1699.17  4877.7 1698.60  4887.9 1698.84
  4893.4 1698.54  4898.5 1698.97  4908.5 1699.17  4935.7 1697.67  4959.9 1697.03
  4978.1 1697.10  4983.2 1695.33  5009.3 1695.09  5009.6 1694.59  5013.1 1694.59
  5013.3 1695.09  5058.4 1697.05  5125.4 1697.66  5172.1 1697.34  5211.2 1697.95
  5227.0 1698.67  5232.6 1698.26  5251.7 1698.21  5306.4 1698.91  5318.3 1699.57
  5350.4 1700.12  5414.7 1699.87  5481.3 1700.62  5500.4 1700.47  5563.9 1701.45
#Mann=3,-1,0
  4781.9    0.05       0  5009.3    0.03       0  5013.3    0.05       0
Bank Sta=5009.3,5013.3
Exp/Cntr=0.3,0.1

Type RM Length L Ch R = 1,5629,86,86,86
BEGIN DESCRIPTION:
Elm 02 31 5628.71
END DESCRIPTION:
XS GIS Cut Line= 4
      1602701.49      6859699.99      1602778.72      6859855.33
      1602806.50      6859882.24      1603013.07      6860045.41
#Sta/Elev= 30
  4787.9 1698.36  4796.8 1698.49  4804.7 1697.57  4810.3 1698.04  4827.1 1697.37
  4832.7 1697.41  4855.1 1697.02  4886.2 1696.94  4899.9 1696.27  4916.7 1695.09
  4930.9 1694.38  4967.8 1694.50  5065.0 1694.35  5065.3 1693.85  5068.8 1693.85
  5069.0 1694.35  5081.5 1694.38  5087.8 1694.86  5102.3 1696.37  5110.3 1698.53
  5124.8 1700.95  5131.2 1701.51  5138.3 1700.51  5145.6 1698.40  5152.0 1697.26
  5180.8 1697.48  5209.7 1698.08  5216.1 1698.52  5230.5 1698.84  5263.3 1699.16
#Mann=3,-1,0
  4787.9    0.05       0  5065.0    0.05       0  5069.0    0.05       0
Bank Sta=5065,5069
Exp/Cntr=0.3,0.1

Type RM Length L Ch R = 1,5543,74,74,74
BEGIN DESCRIPTION:
Elm 02 31 5542.51
END DESCRIPTION:
XS GIS Cut Line= 5
      1602652.86      6859735.56      1602729.24      6859914.36
      1602759.63      6859957.76      1602825.60      6859985.54
      1602965.32      6860085.34
#Sta/Elev= 30
  4806.6 1698.05  4854.2 1696.36  4894.0 1695.68  4894.2 1695.18  4897.7 1695.18
  4898.0 1695.68  4907.1 1696.68  4925.0 1696.75  4930.4 1698.90  4939.7 1700.08
  4948.6 1700.64  4954.1 1700.24  4972.2 1701.54  4977.7 1700.80  5015.7 1701.07
  5021.8 1700.37  5036.6 1701.55  5042.7 1700.92  5051.1 1701.97  5066.4 1700.73
  5071.8 1701.88  5090.1 1700.77  5095.5 1701.92  5113.9 1700.99  5119.3 1702.02
  5140.9 1702.18  5155.6 1699.30  5161.8 1696.75  5176.5 1696.35  5297.3 1698.87
#Mann=3,-1,0
  4806.6    0.05       0  4894.0    0.05       0  4898.0    0.05       0
Bank Sta=4894,4898
Exp/Cntr=0.3,0.1

Type RM Length L Ch R = 1,5469,310,310,310
BEGIN DESCRIPTION:
Elm 02 31 5469.44
END DESCRIPTION:
XS GIS Cut Line= 5
      1602612.04      6859778.47      1602678.03      6859929.55
      1602703.20      6859979.90      1602762.23      6860036.32
      1602905.46      6860097.08
#Sta/Elev= 30
  4779.6 1697.61  4826.3 1696.93  4844.3 1696.52  4849.7 1695.97  4855.5 1695.72
  4873.1 1695.65  4878.6 1695.17  4888.2 1694.94  4920.0 1695.02  4925.4 1695.24
  4954.2 1694.71  4976.6 1694.62  4993.3 1694.76  4995.2 1694.14  4995.4 1693.64
  4998.9 1693.64  4999.2 1694.14  5021.9 1694.17  5029.1 1694.68  5043.2 1695.05
  5078.5 1694.91  5095.2 1695.21  5100.6 1695.15  5129.7 1695.81  5153.4 1695.86
  5171.6 1696.23  5177.0 1696.68  5194.0 1696.97  5206.1 1697.52  5238.0 1697.86
#Mann=3,-1,0
  4779.6    0.05       0  4995.2    0.05       0  4999.2    0.05       0
Bank Sta=4995.2,4999.2
Exp/Cntr=0.3,0.1

Type RM Length L Ch R = 1,5159,298,298,298
BEGIN DESCRIPTION:
Elm 02 31 5158.5
END DESCRIPTION:
XS GIS Cut Line= 3
      1602323.14      6859857.84      1602455.10      6860135.65
      1602512.38      6860350.90
#Sta/Elev= 30
  4695.9 1696.05  4729.3 1695.49  4786.0 1695.33  4871.4 1693.99  4906.4 1693.97
  4916.8 1693.28  4922.3 1693.45  4928.6 1693.04  4945.1 1692.95  4950.7 1693.41
  4973.3 1693.12  4988.5 1692.43  4988.8 1691.93  4992.3 1691.93  4992.5 1692.43
  5016.2 1692.77  5036.9 1693.57  5047.3 1693.52  5056.9 1693.99  5062.1 1693.87
  5068.0 1694.29  5088.7 1694.80  5097.1 1695.24  5130.1 1695.88  5137.2 1696.47
  5171.5 1698.13  5177.3 1698.91  5182.5 1698.54  5192.2 1699.08  5226.2 1699.19
#Mann=3,-1,0
  4695.9    0.05       0  4988.5    0.05       0  4992.5    0.05       0
Bank Sta=4988.5,4992.5
Exp/Cntr=0.3,0.1

Type RM Length L Ch R = 1,4861,174,174,174
BEGIN DESCRIPTION:
Elm 02 31 4860.62
END DESCRIPTION:
XS GIS Cut Line= 3
      1602001.97      6859887.39      1602156.49      6860137.39
      1602309.25      6860366.54
#Sta/Elev= 30
  4705.9 1695.92  4738.1 1694.93  4774.8 1694.40  4817.3 1694.09  4853.9 1693.41
  4896.5 1693.27  4906.0 1692.84  4918.2 1692.77  4927.2 1692.25  4941.7 1692.08
  4948.5 1691.52  4954.4 1691.57  4963.9 1690.94  4977.0 1690.73  4985.2 1691.11
  5003.0 1691.15  5004.3 1690.73  5004.6 1690.23  5008.1 1690.23  5008.3 1690.73
  5012.5 1691.55  5021.4 1691.84  5057.4 1692.02  5084.7 1692.84  5114.5 1693.11
  5120.7 1693.55  5135.5 1693.39  5144.5 1693.93  5201.6 1694.63  5275.2 1696.27
#Mann=3,-1,0
  4705.9    0.05       0  5004.3    0.05       0  5008.3    0.05       0
Bank Sta=5004.3,5008.3
Exp/Cntr=0.3,0.1