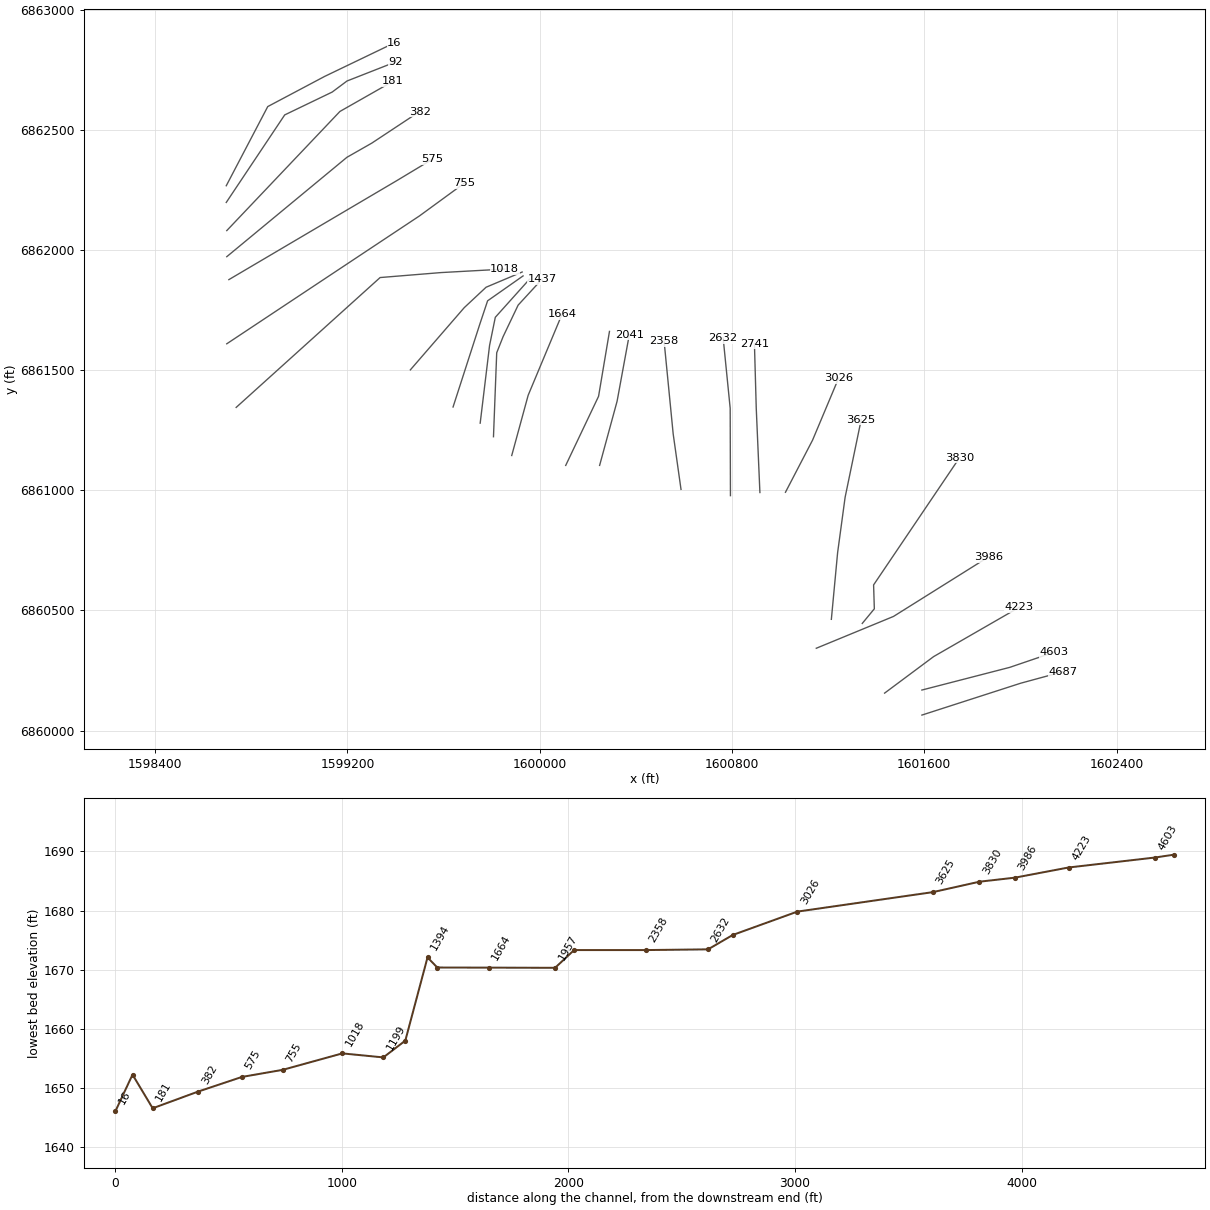
HEC-RAS study Elm 02 31.prj: Elm 02 31 Base Level Engineering

--- Elm 02 31.g01 (geometry) --- (continued)

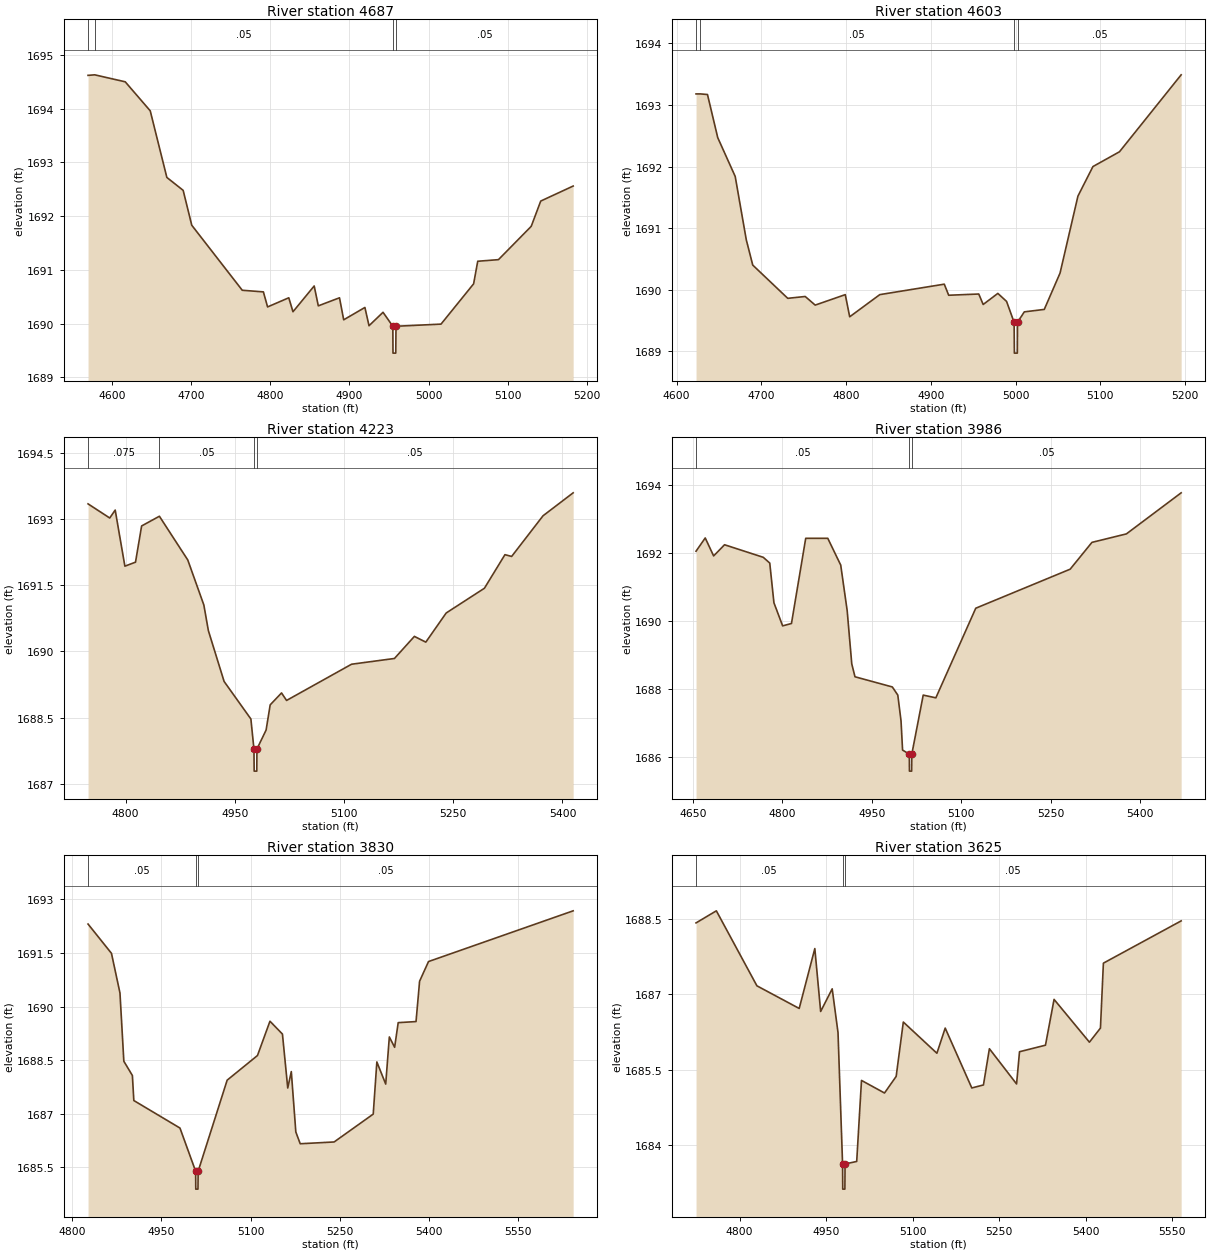
Type RM Length L Ch R = 1,4687,84,84,84
BEGIN DESCRIPTION:
Elm 02 31 4687.41
END DESCRIPTION:
XS GIS Cut Line= 3
      1601590.23      6860064.60      1602001.45      6860197.20
      1602176.13      6860244.71
#Sta/Elev= 30
  4569.7 1694.62  4578.1 1694.63  4616.7 1694.50  4648.3 1693.96  4669.3 1692.72
  4689.9 1692.48  4700.8 1691.83  4764.6 1690.62  4791.3 1690.59  4796.6 1690.31
  4823.4 1690.48  4828.7 1690.22  4855.5 1690.70  4860.7 1690.33  4887.5 1690.48
  4892.8 1690.07  4919.6 1690.30  4924.8 1689.96  4942.5 1690.21  4954.9 1689.95
  4955.1 1689.45  4958.6 1689.45  4958.9 1689.95  5015.8 1689.99  5057.0 1690.74
  5062.2 1691.16  5088.4 1691.19  5129.8 1691.81  5141.8 1692.28  5182.8 1692.56
#Mann=4,-1,0
  4569.7   0.075       0  4578.1    0.05       0  4954.9    0.05       0
  4958.9    0.05       0
Bank Sta=4954.9,4958.9
Exp/Cntr=0.3,0.1

Type RM Length L Ch R = 1,4603,380,380,380
BEGIN DESCRIPTION:
Elm 02 31 4603.3
END DESCRIPTION:
XS GIS Cut Line= 3
      1601590.25      6860168.77      1601955.91      6860263.17
      1602140.23      6860326.05
#Sta/Elev= 30
  4622.9 1693.18  4628.1 1693.18  4636.4 1693.17  4648.5 1692.47  4669.1 1691.84
  4682.2 1690.81  4689.8 1690.40  4731.1 1689.86  4751.7 1689.89  4763.5 1689.75
  4799.0 1689.92  4804.2 1689.56  4839.7 1689.92  4915.8 1690.09  4921.0 1689.91
  4956.5 1689.93  4961.7 1689.76  4979.0 1689.94  4989.3 1689.81  4998.2 1689.47
  4998.5 1688.97  5002.0 1688.97  5002.2 1689.47  5010.2 1689.64  5033.8 1689.68
  5052.4 1690.27  5073.5 1691.52  5091.2 1692.00  5122.5 1692.24  5195.3 1693.49
#Mann=4,-1,0
  4622.9   0.075       0  4628.1    0.05       0  4998.2    0.05       0
  5002.2    0.05       0
Bank Sta=4998.2,5002.2
Exp/Cntr=0.3,0.1

Type RM Length L Ch R = 1,4223,237,237,237
BEGIN DESCRIPTION:
Elm 02 31 4222.66
END DESCRIPTION:
XS GIS Cut Line= 3
      1601435.08      6860155.99      1601639.04      6860307.88
      1601996.18      6860513.50
#Sta/Elev= 30
  4748.3 1693.34  4778.1 1693.02  4785.6 1693.20  4798.9 1691.93  4813.5 1692.02
  4821.9 1692.84  4846.3 1693.06  4885.3 1692.07  4907.4 1691.05  4913.6 1690.47
  4935.2 1689.32  4972.0 1688.47  4976.2 1687.79  4976.5 1687.29  4980.1 1687.29
  4980.3 1687.79  4992.9 1688.22  4998.5 1688.79  5014.1 1689.06  5021.0 1688.89
  5110.3 1689.71  5169.2 1689.84  5196.6 1690.34  5212.3 1690.21  5240.3 1690.87
  5292.8 1691.43  5321.0 1692.19  5330.2 1692.15  5373.3 1693.07  5414.7 1693.59
#Mann=4,-1,0
  4748.3   0.075       0  4846.3    0.05       0  4976.2    0.05       0
  4980.3    0.05       0
Bank Sta=4976.2,4980.3
Exp/Cntr=0.3,0.1

Type RM Length L Ch R = 1,3986,156,156,156
BEGIN DESCRIPTION:
Elm 02 31 3985.59
END DESCRIPTION:
XS GIS Cut Line= 3
      1601150.76      6860342.60      1601471.94      6860474.98
      1601866.87      6860722.35
#Sta/Elev= 30
  4655.5 1692.05  4670.9 1692.44  4685.0 1691.91  4703.3 1692.24  4768.2 1691.87
  4779.1 1691.70  4786.1 1690.53  4800.7 1689.85  4815.5 1689.92  4839.4 1692.43
  4876.4 1692.43  4898.1 1691.64  4908.9 1690.30  4916.6 1688.73  4922.0 1688.35
  4984.6 1688.05  4993.8 1687.81  4999.2 1687.05  5001.8 1686.19  5013.1 1686.07
  5013.3 1685.57  5017.0 1685.57  5017.3 1686.07  5036.4 1687.81  5057.6 1687.73
  5124.5 1690.37  5282.8 1691.52  5319.3 1692.31  5377.1 1692.56  5468.9 1693.77
#Mann=3,-1,0
  4655.5    0.05       0  5013.1    0.03       0  5017.3    0.05       0
Bank Sta=5013.1,5017.3
Exp/Cntr=0.3,0.1

Type RM Length L Ch R = 1,3830,205,205,205
BEGIN DESCRIPTION:
Elm 02 31 3829.92
END DESCRIPTION:
XS GIS Cut Line= 4
      1601342.12      6860445.98      1601392.32      6860506.73
      1601389.25      6860606.19      1601746.26      6861134.57
#Sta/Elev= 30
  4826.7 1692.31  4866.1 1691.49  4880.4 1690.38  4886.9 1688.47  4901.3 1688.07
  4903.7 1687.37  4981.3 1686.60  5007.7 1685.39  5007.9 1684.89  5011.6 1684.89
  5011.9 1685.39  5060.7 1687.94  5111.7 1688.63  5132.7 1689.59  5153.7 1689.23
  5162.6 1687.72  5168.6 1688.18  5176.2 1686.49  5183.6 1686.16  5240.6 1686.21
  5306.4 1686.99  5312.5 1688.45  5327.4 1687.83  5333.5 1689.15  5342.4 1688.86
  5348.4 1689.55  5378.4 1689.58  5384.4 1690.71  5399.4 1691.26  5642.7 1692.68
#Mann=3,-1,0
  4826.7    0.05       0  5007.7    0.03       0  5011.9    0.05       0
Bank Sta=5007.7,5011.9
Exp/Cntr=0.3,0.1

Type RM Length L Ch R = 1,3625,599,599,599
BEGIN DESCRIPTION:
Elm 02 31 3624.84
END DESCRIPTION:
XS GIS Cut Line= 4
      1601213.47      6860462.98      1601239.51      6860740.31
      1601270.78      6860971.09      1601337.60      6861293.71
#Sta/Elev= 30
  4724.6 1688.42  4759.8 1688.66  4830.1 1687.17  4903.4 1686.72  4930.5 1687.91
  4940.6 1686.66  4960.6 1687.11  4970.7 1686.24  4978.6 1683.63  4978.9 1683.13
  4982.6 1683.13  4982.9 1683.63  5003.1 1683.68  5011.4 1685.29  5051.3 1685.04
  5071.5 1685.37  5083.9 1686.45  5142.1 1685.83  5156.5 1686.33  5202.6 1685.14
  5222.8 1685.20  5233.1 1685.92  5280.2 1685.22  5285.3 1685.86  5330.3 1685.99
  5345.2 1686.90  5406.5 1686.05  5425.6 1686.33  5430.7 1687.62  5565.5 1688.46
#Mann=3,-1,0
  4724.6    0.05       0  4978.6    0.03       0  4982.9    0.05       0
Bank Sta=4978.6,4982.9
Exp/Cntr=0.3,0.1

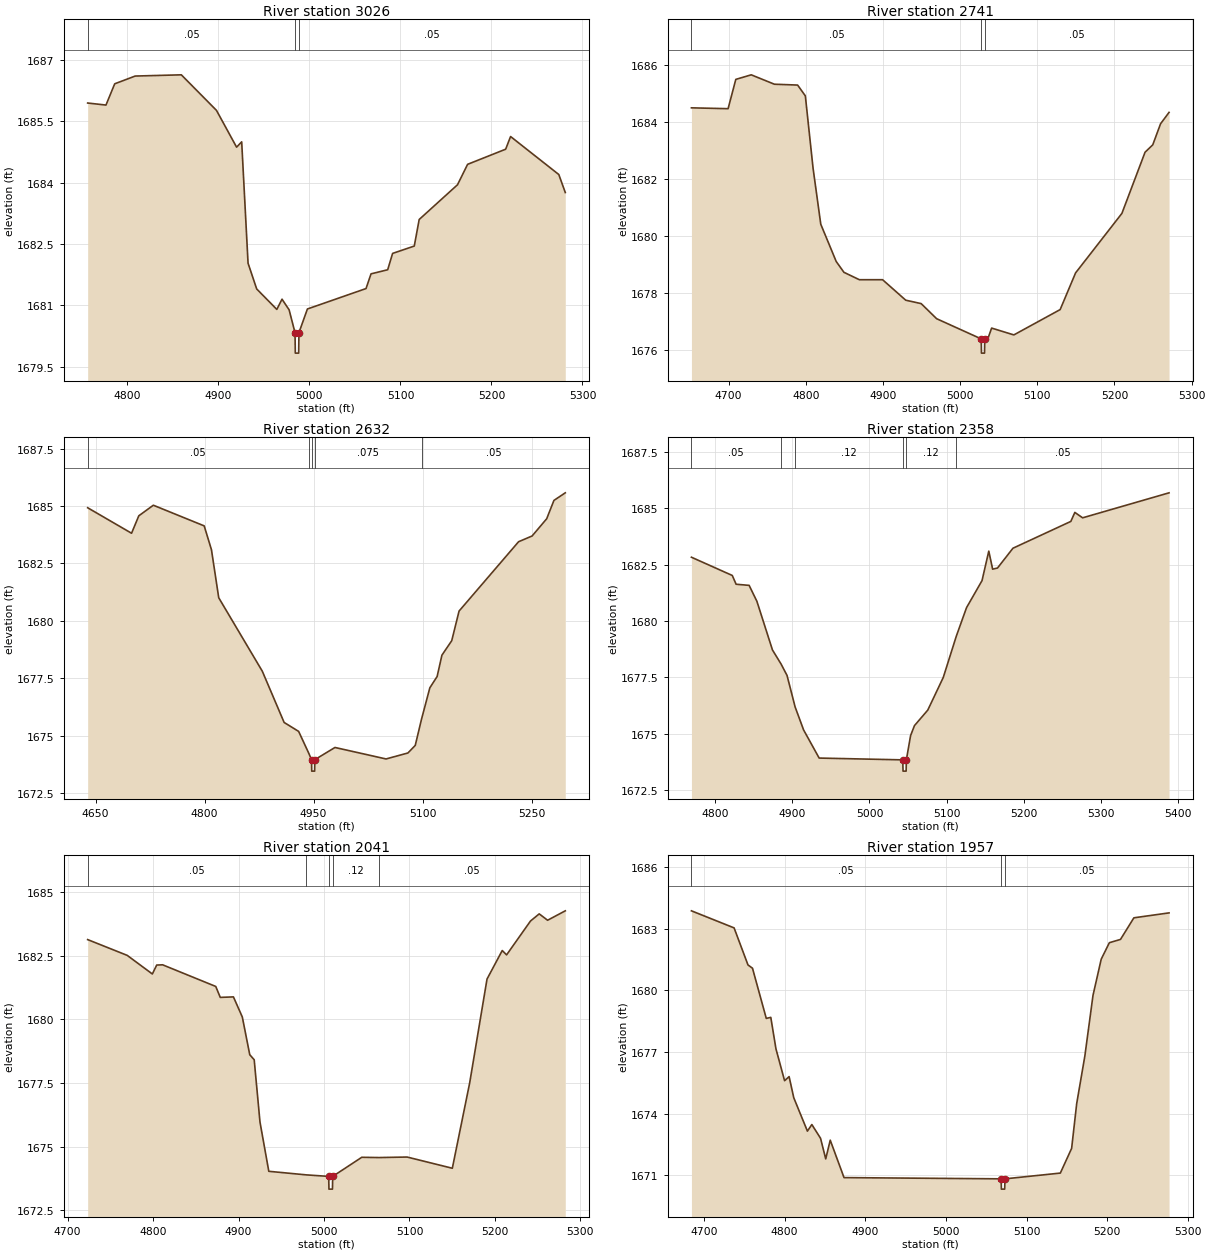
Type RM Length L Ch R = 1,3026,285,285,285
BEGIN DESCRIPTION:
Elm 02 31 3026.32
END DESCRIPTION:
XS GIS Cut Line= 3
      1601022.53      6860991.68      1601135.38      6861208.70
      1601243.87      6861466.92
#Sta/Elev= 30
  4756.4 1685.95  4776.5 1685.90  4786.1 1686.42  4808.6 1686.61  4859.3 1686.64
  4897.9 1685.77  4920.0 1684.87  4925.6 1685.00  4932.6 1682.03  4942.1 1681.40
  4964.2 1680.90  4969.9 1681.15  4977.7 1680.89  4984.2 1680.33  4984.5 1679.83
  4988.2 1679.83  4988.5 1680.33  4997.8 1680.91  5062.2 1681.41  5067.7 1681.77
  5086.0 1681.87  5091.4 1682.27  5115.2 1682.45  5120.6 1683.10  5162.7 1683.95
  5173.8 1684.45  5215.6 1684.82  5221.0 1685.13  5274.0 1684.20  5281.1 1683.76
#Mann=3,-1,0
  4756.4    0.05       0  4984.2    0.03       0  4988.5    0.05       0
Bank Sta=4984.2,4988.5
Exp/Cntr=0.3,0.1

Type RM Length L Ch R = 1,2741,109,109,109
BEGIN DESCRIPTION:
Elm 02 31 2740.73
END DESCRIPTION:
XS GIS Cut Line= 3
      1600916.19      6860990.58      1600901.00      6861339.99
      1600893.41      6861609.04
#Sta/Elev= 30
  4651.8 1684.50  4699.3 1684.47  4709.3 1685.50  4729.3 1685.66  4759.3 1685.33
  4789.4 1685.30  4799.4 1684.92  4809.4 1682.38  4819.4 1680.41  4839.4 1679.10
  4849.4 1678.72  4869.4 1678.46  4899.5 1678.46  4929.5 1677.74  4949.5 1677.62
  4969.5 1677.09  5027.3 1676.38  5027.6 1675.88  5031.6 1675.88  5031.9 1676.38
  5035.8 1676.38  5040.8 1676.76  5069.6 1676.52  5129.6 1677.41  5149.6 1678.70
  5209.6 1680.79  5239.6 1682.94  5249.6 1683.20  5259.7 1683.94  5270.7 1684.34
#Mann=3,-1,0
  4651.8    0.05       0  5027.3    0.05       0  5031.9    0.05       0
Bank Sta=5027.3,5031.9
Exp/Cntr=0.3,0.1

Type RM Length L Ch R = 1,2632,274,274,274
BEGIN DESCRIPTION:
Elm 02 31 2632.17
END DESCRIPTION:
XS GIS Cut Line= 3
      1600793.58      6860977.58      1600792.50      6861341.08
      1600763.25      6861633.52
#Sta/Elev= 30
  4639.1 1684.92  4699.5 1683.81  4709.5 1684.57  4729.5 1685.03  4799.5 1684.13
  4809.5 1683.09  4819.5 1681.00  4879.5 1677.80  4909.5 1675.57  4929.5 1675.18
  4943.4 1674.23  4947.2 1673.95  4947.5 1673.45  4951.5 1673.45  4951.8 1673.95
  4979.5 1674.48  5049.8 1673.98  5079.9 1674.24  5090.0 1674.57  5098.6 1675.71
  5110.1 1677.08  5120.1 1677.57  5126.7 1678.50  5140.2 1679.13  5150.3 1680.42
  5232.2 1683.44  5250.8 1683.69  5270.9 1684.44  5280.9 1685.24  5296.5 1685.57
#Mann=5,-1,0
  4639.1    0.05       0  4943.4   0.075       0  4947.2    0.07       0
  4951.8   0.075       0  5098.6    0.05       0
Bank Sta=4947.2,4951.8
Exp/Cntr=0.3,0.1

Type RM Length L Ch R = 1,2358,317,317,317
BEGIN DESCRIPTION:
Elm 02 31 2358.04
END DESCRIPTION:
XS GIS Cut Line= 3
      1600587.86      6861003.80      1600555.31      6861234.27
      1600517.55      6861619.67
#Sta/Elev= 30
  4768.9 1682.83  4821.9 1682.02  4826.9 1681.63  4843.8 1681.58  4853.9 1680.87
  4874.1 1678.71  4885.2 1678.09  4893.0 1677.58  4903.5 1676.18  4914.5 1675.16
  4934.7 1673.91  5043.2 1673.83  5043.6 1673.33  5047.6 1673.33  5047.9 1673.83
  5053.4 1674.91  5058.4 1675.35  5075.7 1676.04  5095.8 1677.49  5112.8 1679.33
  5126.0 1680.59  5146.1 1681.79  5154.9 1683.10  5159.9 1682.30  5166.2 1682.35
  5186.3 1683.23  5261.4 1684.42  5266.6 1684.82  5276.7 1684.58  5388.9 1685.69
#Mann=6,-1,0
  4768.9    0.05       0  4885.2   0.075       0  4903.5    0.12       0
  5043.2    0.07       0  5047.9    0.12       0  5112.8    0.05       0
Bank Sta=5043.2,5047.9
Exp/Cntr=0.3,0.1

Type RM Length L Ch R = 1,2041,84,84,84
BEGIN DESCRIPTION:
Elm 02 31 2040.77
END DESCRIPTION:
XS GIS Cut Line= 3
      1600249.19      6861103.41      1600321.88      6861370.31
      1600372.87      6861648.05
#Sta/Elev= 30
  4723.4 1683.13  4769.7 1682.51  4799.1 1681.78  4804.2 1682.13  4811.1 1682.14
  4873.3 1681.29  4878.6 1680.86  4894.0 1680.88  4904.4 1680.09  4913.1 1678.61
  4918.3 1678.41  4925.1 1675.96  4935.4 1674.03  4979.2 1673.89  5005.5 1673.83
  5005.8 1673.33  5009.9 1673.33  5010.2 1673.83  5044.2 1674.58  5064.3 1674.57
  5097.3 1674.59  5150.2 1674.15  5170.5 1677.50  5190.8 1681.58  5208.6 1682.70
  5213.7 1682.53  5241.7 1683.86  5251.9 1684.14  5261.7 1683.89  5282.4 1684.26
#Mann=5,-1,0
  4723.4    0.05       0  4979.2    0.12       0  5005.5    0.07       0
  5010.2    0.12       0  5064.3    0.05       0
Bank Sta=5005.5,5010.2
Exp/Cntr=0.3,0.1

Type RM Length L Ch R = 1,1957,293,293,293
BEGIN DESCRIPTION:
Elm 02 31 1957.46
END DESCRIPTION:
XS GIS Cut Line= 3
      1600108.13      6861103.39      1600244.84      6861390.92
      1600290.20      6861660.96
#Sta/Elev= 30
  4684.4 1683.86  4737.3 1683.03  4754.5 1681.23  4760.1 1681.07  4777.2 1678.63
  4782.8 1678.68  4789.2 1677.15  4799.9 1675.60  4805.5 1675.80  4811.3 1674.77
  4828.2 1673.15  4833.7 1673.47  4844.5 1672.80  4850.9 1671.80  4856.5 1672.71
  4873.6 1670.89  5068.4 1670.83  5068.7 1670.33  5072.8 1670.33  5073.2 1670.83
  5141.8 1671.11  5155.8 1672.31  5162.1 1674.49  5172.2 1676.80  5182.3 1679.75
  5192.5 1681.51  5202.6 1682.31  5216.4 1682.47  5233.0 1683.52  5276.6 1683.76
#Mann=3,-1,0
  4684.4    0.05       0  5068.4    0.05       0  5073.2    0.05       0
Bank Sta=5068.4,5073.2
Exp/Cntr=0.3,0.1

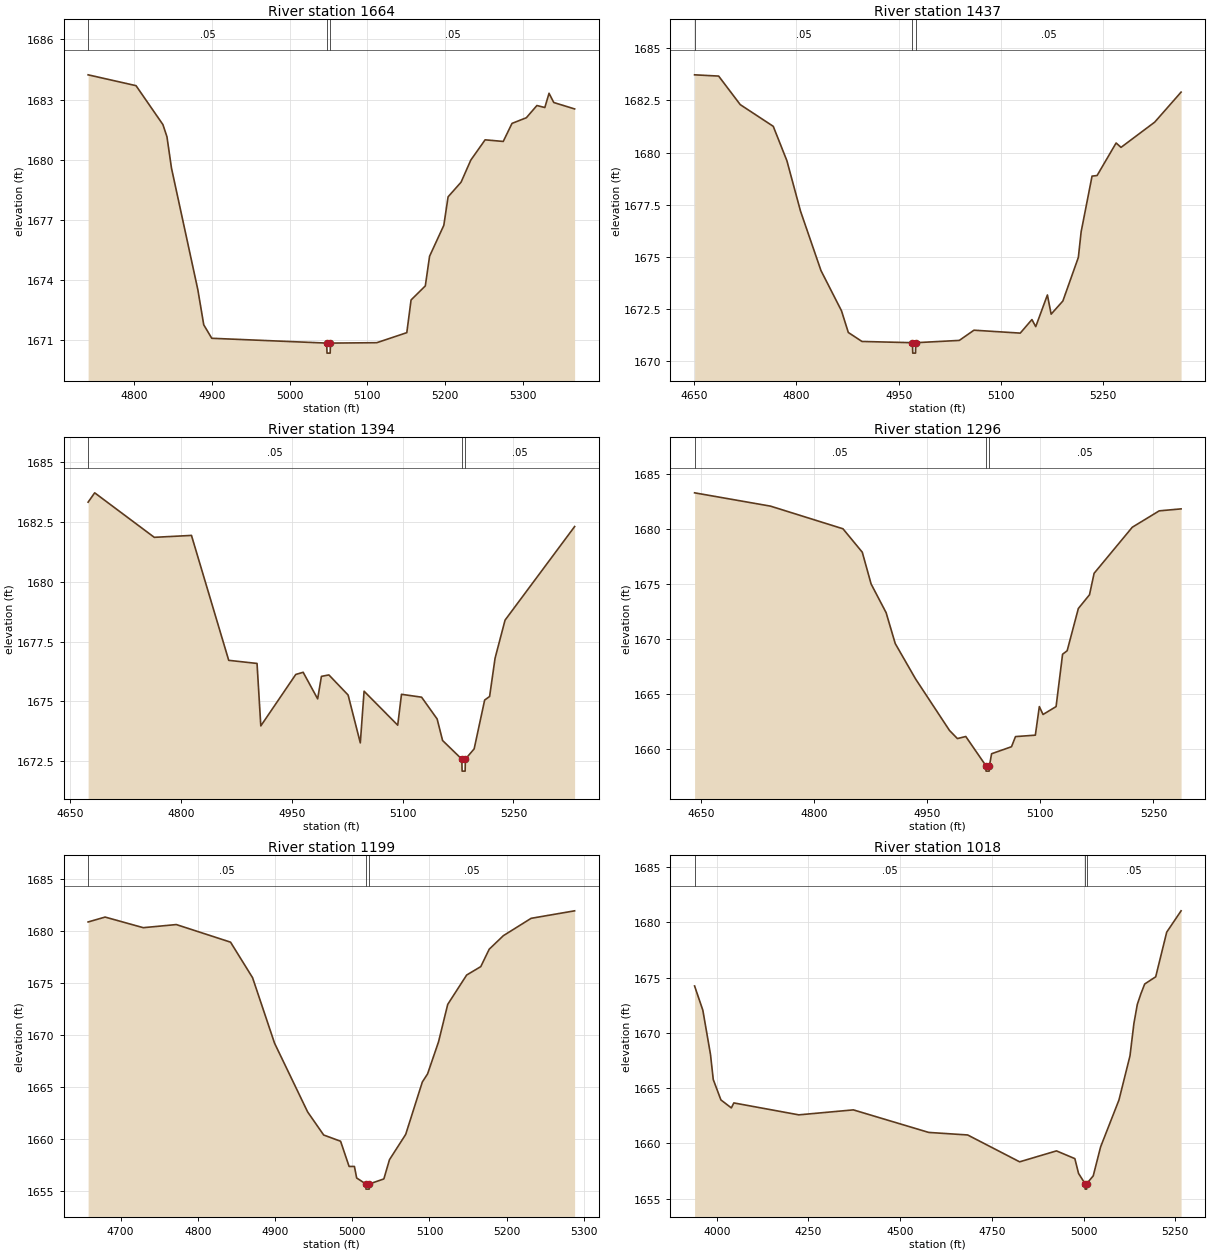
Type RM Length L Ch R = 1,1664,227,227,227
BEGIN DESCRIPTION:
Elm 02 31 1664.27
END DESCRIPTION:
XS GIS Cut Line= 3
      1599883.50      6861144.59      1599951.87      6861395.26
      1600092.94      6861732.74
#Sta/Elev= 30
  4741.0 1684.23  4802.6 1683.69  4837.2 1681.75  4842.4 1681.14  4848.2 1679.58
  4882.1 1673.52  4889.7 1671.77  4900.0 1671.10  5047.8 1670.86  5048.2 1670.36
  5052.3 1670.36  5052.6 1670.86  5112.2 1670.88  5150.8 1671.38  5156.3 1673.01
  5174.6 1673.71  5180.1 1675.19  5198.4 1676.73  5203.9 1678.15  5220.6 1678.88
  5233.1 1679.98  5251.5 1680.99  5274.8 1680.91  5286.1 1681.81  5304.5 1682.09
  5318.1 1682.70  5328.3 1682.60  5333.7 1683.31  5339.8 1682.85  5366.6 1682.53
#Mann=3,-1,0
  4741.0    0.05       0  5047.8    0.05       0  5052.6    0.05       0
Bank Sta=5047.8,5052.6
Exp/Cntr=0.3,0.1

Type RM Length L Ch R = 1,1437,43,43,43
BEGIN DESCRIPTION:
Elm 02 31 1436.86
END DESCRIPTION:
XS GIS Cut Line= 5
      1599807.55      6861222.70      1599821.01      6861572.17
      1599847.70      6861639.40      1599910.15      6861770.36
      1600009.35      6861878.09
#Sta/Elev= 30
  4650.7 1683.73  4686.0 1683.67  4717.7 1682.30  4766.1 1681.26  4786.1 1679.61
  4806.1 1677.19  4836.1 1674.34  4866.2 1672.41  4876.2 1671.37  4896.2 1670.94
  4970.3 1670.88  4970.7 1670.38  4974.8 1670.38  4975.1 1670.88  5039.0 1670.99
  5060.5 1671.48  5128.4 1671.34  5145.5 1671.99  5151.1 1671.65  5168.2 1673.17
  5173.7 1672.25  5190.9 1672.88  5213.6 1674.97  5217.7 1676.20  5233.7 1678.87
  5241.1 1678.90  5269.0 1680.46  5276.2 1680.25  5325.6 1681.46  5364.3 1682.90
#Mann=3,-1,0
  4650.7    0.05       0  4970.3    0.05       0  4975.1    0.05       0
Bank Sta=4970.3,4975.1
Exp/Cntr=0.3,0.1

Type RM Length L Ch R = 1,1394,98,98,98
BEGIN DESCRIPTION:
Elm 02 31 1394.29
END DESCRIPTION:
XS GIS Cut Line= 4
      1599752.22      6861279.18      1599791.28      6861602.51
      1599815.15      6861719.70      1599957.28      6861878.10
#Sta/Elev= 30
  4674.6 1683.33  4683.5 1683.72  4764.1 1681.86  4814.4 1681.94  4864.8 1676.72
  4903.1 1676.59  4908.2 1673.98  4955.5 1676.13  4965.5 1676.22  4985.1 1675.11
  4990.2 1676.05  5000.3 1676.11  5026.3 1675.27  5042.8 1673.27  5047.9 1675.43
  5093.4 1674.01  5098.5 1675.30  5125.7 1675.18  5146.7 1674.27  5154.1 1673.37
  5180.1 1672.59  5180.5 1672.09  5184.6 1672.09  5184.9 1672.59  5196.8 1673.02
  5211.0 1675.06  5217.7 1675.21  5225.1 1676.81  5238.6 1678.40  5332.7 1682.31
#Mann=3,-1,0
  4674.6    0.05       0  5180.1    0.05       0  5184.9    0.05       0
Bank Sta=5180.1,5184.9
Exp/Cntr=0.3,0.1

Type RM Length L Ch R = 1,1296,97,97,97
BEGIN DESCRIPTION:
Elm 02 31 1295.95
END DESCRIPTION:
XS GIS Cut Line= 4
      1599639.36      6861346.41      1599749.83      6861688.49
      1599783.08      6861788.26      1599930.65      6861891.80
#Sta/Elev= 30
  4641.7 1683.33  4742.3 1682.12  4838.4 1680.06  4864.0 1677.93  4875.7 1675.04
  4895.6 1672.43  4907.7 1669.62  4934.5 1666.42  4979.6 1661.72  4990.1 1660.98
  5001.2 1661.17  5027.8 1658.52  5028.1 1658.02  5032.2 1658.02  5032.6 1658.52
  5035.4 1659.60  5061.8 1660.24  5067.1 1661.16  5093.4 1661.29  5098.7 1663.89
  5103.6 1663.17  5120.9 1663.89  5129.5 1668.65  5135.6 1668.97  5150.4 1672.81
  5165.2 1674.06  5171.3 1676.01  5221.9 1680.20  5257.6 1681.69  5286.6 1681.87
#Mann=3,-1,0
  4641.7    0.05       0  5027.8    0.05       0  5032.6    0.05       0
Bank Sta=5027.8,5032.6
Exp/Cntr=0.3,0.1

Type RM Length L Ch R = 1,1199,181,181,181
BEGIN DESCRIPTION:
Elm 02 31 1198.81
END DESCRIPTION:
XS GIS Cut Line= 4
      1599461.63      6861500.90      1599685.77      6861759.67
      1599776.74      6861844.74      1599926.92      6861908.11
#Sta/Elev= 30
  4658.0 1680.85  4680.0 1681.32  4729.4 1680.30  4772.2 1680.60  4842.4 1678.91
  4870.9 1675.50  4899.4 1669.20  4942.2 1662.60  4963.0 1660.38  4984.9 1659.78
  4995.9 1657.36  5002.8 1657.36  5005.7 1656.25  5017.5 1655.68  5017.8 1655.18
  5021.9 1655.18  5022.3 1655.68  5040.9 1656.16  5048.2 1658.01  5069.2 1660.44
  5090.7 1665.47  5097.5 1666.25  5111.7 1669.33  5123.6 1672.93  5148.1 1675.75
  5166.4 1676.56  5177.3 1678.23  5195.6 1679.53  5231.6 1681.20  5287.9 1681.92
#Mann=3,-1,0
  4658.0    0.05       0  5017.5    0.05       0  5022.3    0.05       0
Bank Sta=5017.5,5022.3
Exp/Cntr=0.3,0.1

Type RM Length L Ch R = 1,1018,263,263,263
BEGIN DESCRIPTION:
Elm 02 31 1017.8
END DESCRIPTION:
XS GIS Cut Line= 4
      1598736.86      6861344.71      1599335.79      6861885.05
      1599588.82      6861905.71      1599854.10      6861920.30
#Sta/Elev= 30
  3939.6 1674.24  3962.1 1672.05  3983.0 1668.04  3990.5 1665.78  4011.4 1663.93
  4039.8 1663.21  4046.6 1663.66  4223.7 1662.58  4372.4 1663.03  4577.9 1660.99
  4684.0 1660.76  4825.7 1658.33  4926.1 1659.32  4976.2 1658.62  4986.3 1657.28
  5003.9 1656.36  5004.3 1655.86  5008.4 1655.86  5008.7 1656.36  5026.3 1657.06
  5046.4 1659.68  5096.4 1663.92  5126.5 1667.92  5137.2 1670.85  5146.5 1672.58
  5156.5 1673.56  5166.6 1674.42  5196.6 1675.07  5226.6 1679.11  5265.8 1681.04
#Mann=3,-1,0
  3939.6    0.05       0  5003.9    0.05       0  5008.7    0.05       0
Bank Sta=5003.9,5008.7
Exp/Cntr=0.3,0.1

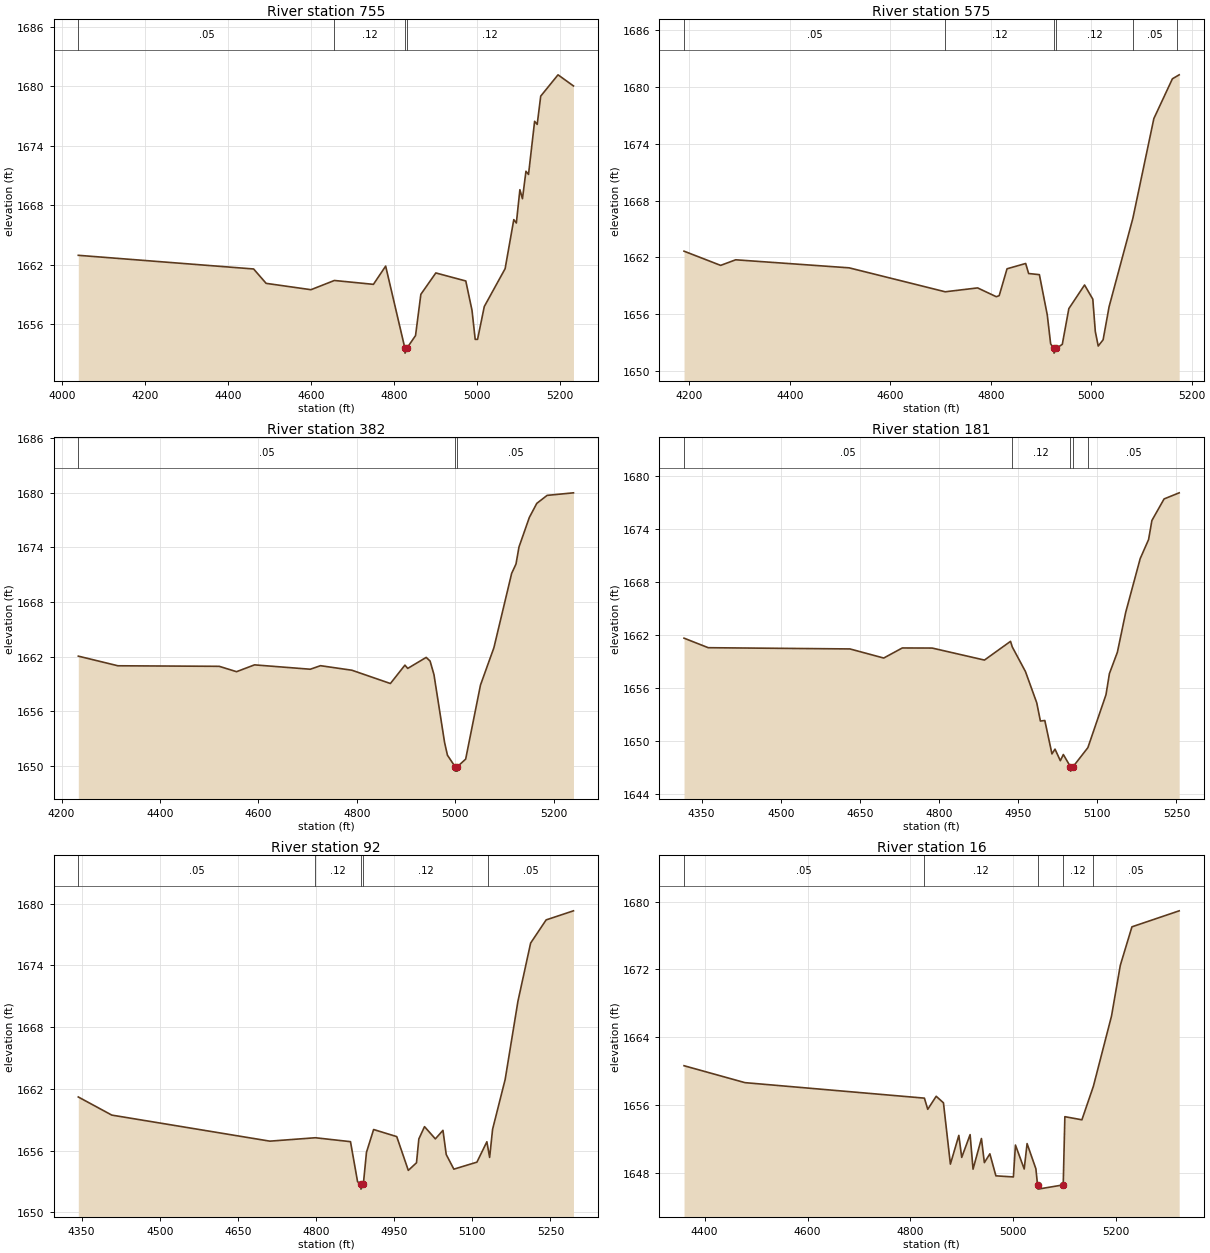
Type RM Length L Ch R = 1,755,180,180,180
BEGIN DESCRIPTION:
Elm 02 31 754.6
END DESCRIPTION:
XS GIS Cut Line= 3
      1598697.73      6861609.41      1599499.59      6862141.48
      1599686.20      6862277.75
#Sta/Elev= 30
  4039.0 1662.95  4461.6 1661.57  4491.7 1660.12  4599.8 1659.48  4656.2 1660.41
  4750.3 1660.02  4779.8 1661.86  4826.1 1653.58  4826.5 1653.08  4831.0 1653.58
  4851.8 1654.85  4864.6 1659.01  4900.7 1661.17  4972.9 1660.36  4987.9 1657.40
  4995.6 1654.47  5001.3 1654.47  5017.5 1657.78  5067.7 1661.60  5088.6 1666.55
  5094.8 1666.21  5103.3 1669.57  5109.5 1668.66  5117.9 1671.43  5124.1 1671.11
  5138.8 1676.47  5145.0 1676.16  5153.5 1679.01  5195.2 1681.16  5232.4 1680.04
#Mann=4,-1,0
  4039.0    0.05       0  4656.2    0.12       0  4826.1    0.07       0
  4831.0    0.12       0
Bank Sta=4826.1,4831
Exp/Cntr=0.3,0.1

Type RM Length L Ch R = 1,575,193,193,193
BEGIN DESCRIPTION:
Elm 02 31 575.23
END DESCRIPTION:
XS GIS Cut Line= 3
      1598706.48      6861876.38      1599404.57      6862287.92
      1599554.54      6862378.18
#Sta/Elev= 30
  4189.7 1662.65  4262.6 1661.15  4292.5 1661.74  4518.3 1660.89  4709.5 1658.36
  4774.0 1658.77  4811.1 1657.84  4816.9 1657.95  4832.5 1660.79  4869.6 1661.35
  4875.5 1660.29  4896.9 1660.17  4912.6 1655.91  4919.3 1652.86  4925.7 1652.38
  4926.1 1651.88  4930.7 1652.38  4942.5 1652.81  4955.5 1656.58  4986.8 1659.08
  5003.2 1657.58  5008.2 1654.16  5014.0 1652.63  5023.7 1653.29  5035.6 1656.78
  5082.9 1666.12  5124.7 1676.66  5161.6 1680.86  5171.2 1681.16  5175.1 1681.28
#Mann=6,-1,0
  4189.7    0.05       0  4709.5    0.12       0  4925.7    0.07       0
  4930.7    0.12       0  5082.9    0.05       0  5171.2    0.12       0
Bank Sta=4925.7,4930.7
Exp/Cntr=0.3,0.1

Type RM Length L Ch R = 1,382,201,201,201
BEGIN DESCRIPTION:
Elm 02 31 381.8
END DESCRIPTION:
XS GIS Cut Line= 4
      1598697.78      6861971.86      1599197.75      6862385.39
      1599301.21      6862444.39      1599499.79      6862575.69
#Sta/Elev= 30
  4234.0 1662.05  4314.5 1660.99  4520.3 1660.93  4555.5 1660.34  4592.0 1661.09
  4705.3 1660.61  4726.1 1661.00  4789.9 1660.50  4868.1 1659.04  4897.6 1661.06
  4903.3 1660.70  4940.8 1661.91  4948.7 1661.51  4956.6 1660.02  4978.2 1652.55
  4984.0 1651.16  4999.4 1649.91  4999.8 1649.41  5004.0 1649.41  5004.4 1649.91
  5021.0 1650.73  5051.1 1658.87  5078.4 1662.98  5114.4 1671.14  5123.3 1672.18
  5129.3 1674.04  5150.4 1677.30  5165.5 1678.84  5186.5 1679.72  5240.0 1680.00
#Mann=3,-1,0
  4234.0    0.05       0  4999.4    0.05       0  5004.4    0.05       0
Bank Sta=4999.4,5004.4
Exp/Cntr=0.3,0.1

Type RM Length L Ch R = 1,181,89,89,89
BEGIN DESCRIPTION:
Elm 02 31 180.98
END DESCRIPTION:
XS GIS Cut Line= 3
      1598697.78      6862080.37      1599168.54      6862576.12
      1599389.90      6862701.99
#Sta/Elev= 30
  4316.8 1661.63  4362.7 1660.55  4631.3 1660.41  4695.2 1659.38  4730.4 1660.52
  4787.0 1660.51  4886.1 1659.15  4935.5 1661.27  4938.8 1660.64  4963.8 1657.85
  4985.2 1654.31  4992.1 1652.25  5000.5 1652.31  5014.0 1648.53  5019.8 1649.07
  5029.9 1647.76  5035.6 1648.46  5049.0 1647.08  5049.4 1646.58  5054.0 1647.08
  5082.1 1649.24  5116.4 1655.23  5122.9 1657.62  5138.0 1660.04  5153.8 1664.56
  5181.2 1670.63  5197.1 1672.79  5203.4 1674.95  5226.5 1677.39  5255.1 1678.08
#Mann=5,-1,0
  4316.8    0.05       0  4938.8    0.12       0  5049.0    0.07       0
  5054.0    0.12       0  5082.1    0.05       0
Bank Sta=5049,5054
Exp/Cntr=0.3,0.1

Type RM Length L Ch R = 1,92,76,76,76
BEGIN DESCRIPTION:
Elm 02 31 91.56
END DESCRIPTION:
XS GIS Cut Line= 5
      1598695.60      6862197.55      1598938.83      6862561.75
      1599136.43      6862656.85      1599198.06      6862702.85
      1599399.47      6862781.85
#Sta/Elev= 30
  4343.6 1661.22  4407.9 1659.46  4711.3 1656.93  4798.7 1657.26  4866.1 1656.88
  4879.7 1652.99  4885.8 1652.77  4886.2 1652.27  4890.8 1652.77  4896.8 1655.85
  4910.5 1658.06  4954.9 1657.37  4977.1 1654.09  4992.8 1654.83  4997.3 1657.14
  5008.2 1658.34  5029.0 1657.15  5043.6 1657.98  5049.9 1655.63  5064.5 1654.21
  5108.8 1654.89  5127.9 1656.87  5130.3 1656.18  5133.2 1655.35  5138.9 1658.09
  5163.0 1662.92  5187.5 1670.51  5211.9 1676.17  5241.7 1678.42  5294.1 1679.30
#Mann=5,-1,0
  4343.6    0.05       0  4798.7    0.12       0  4885.8    0.07       0
  4890.8    0.12       0  5130.3    0.05       0
Bank Sta=4885.8,4890.8
Exp/Cntr=0.3,0.1

Type RM Length L Ch R = 1,16,0,0,0
BEGIN DESCRIPTION:
Elm 02 31 976.764
END DESCRIPTION:
XS GIS Cut Line= 4
      1598695.62      6862267.03      1598868.27      6862596.45
      1599105.05      6862721.95      1599395.34      6862861.52
#Sta/Elev= 30
  4360.1 1660.62  4478.5 1658.62  4827.1 1656.79  4833.6 1655.47  4850.0 1657.01
  4864.1 1656.24  4877.6 1648.99  4894.0 1652.39  4899.6 1649.79  4915.9 1652.48
  4921.6 1648.40  4937.9 1652.02  4943.6 1649.17  4954.3 1650.21  4966.0 1647.61
  5000.0 1647.48  5004.0 1651.25  5021.0 1648.42  5026.6 1651.42  5043.7 1648.44
  5046.9 1646.54  5047.9 1646.04  5096.8 1646.54  5100.0 1654.60  5133.1 1654.23
  5155.4 1658.19  5190.6 1666.48  5207.7 1672.48  5230.3 1677.03  5322.1 1678.92
#Mann=5,-1,0
  4360.1    0.05       0  4827.1    0.12       0  5046.9    0.07       0
  5096.8    0.12       0  5155.4    0.05       0
Bank Sta=5046.9,5096.8
Exp/Cntr=0.3,0.1

Chan Stop Cuts=-1