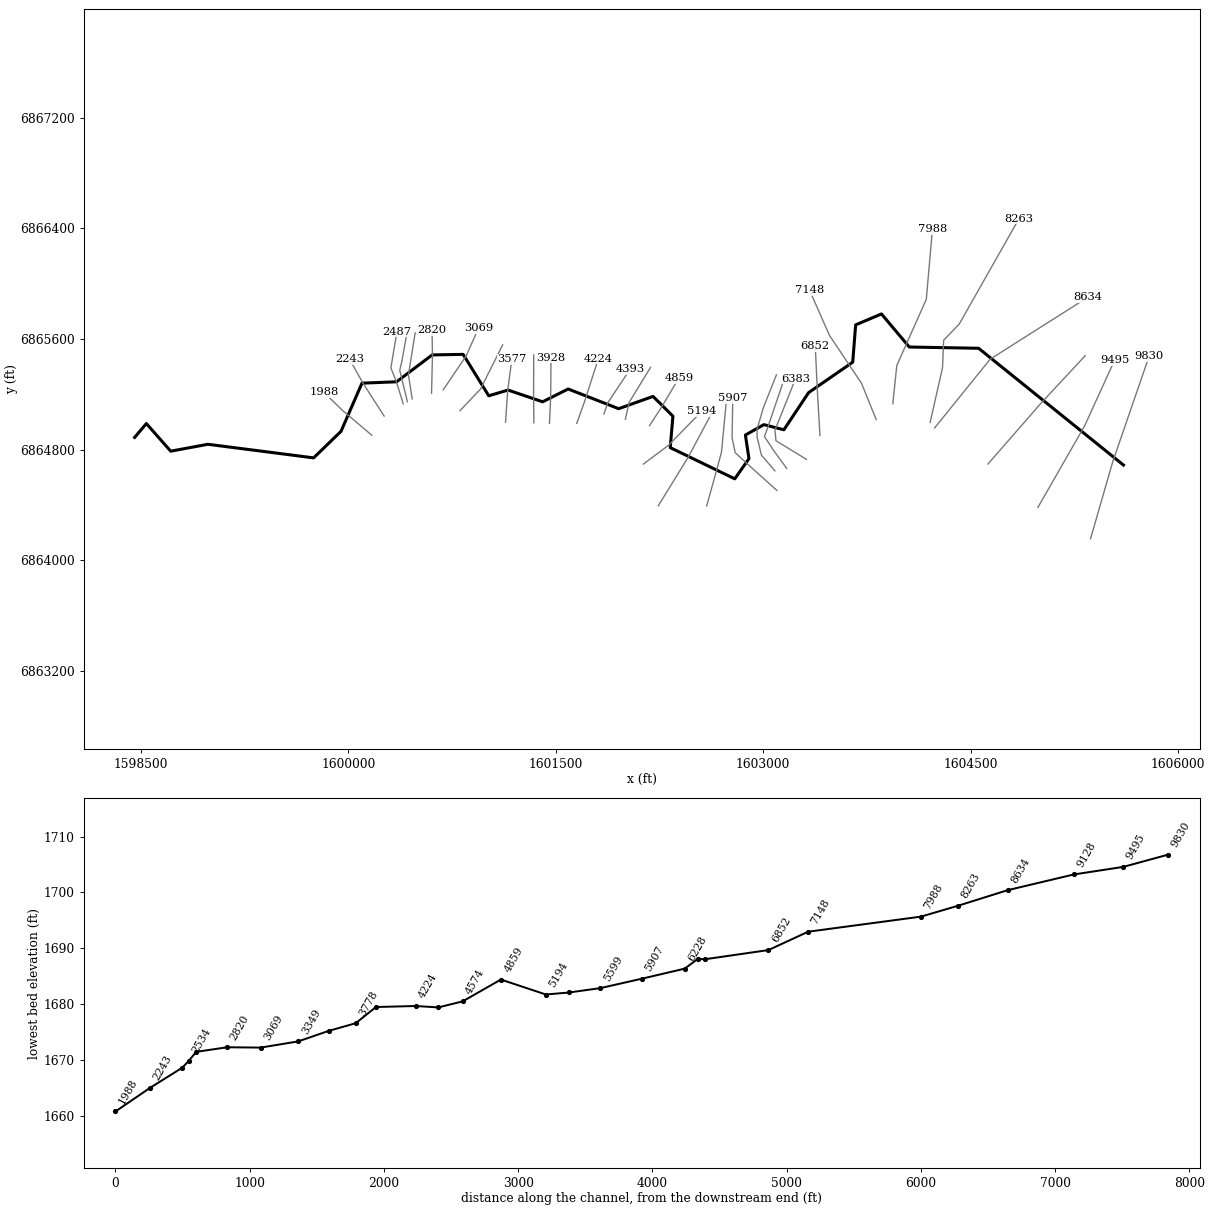
--- Elm 02 32.prj (project) ---

Proj Title=Elm 02 32 Base Level Engineering
Current Plan=p01
Default Exp/Contr=0.3,0.1
English Units
Geom File=g01
Flow File=f01
Plan File=p01
Y Axis Title=Elevation
X Axis Title(PF)=Main Channel Distance
X Axis Title(XS)=Station
BEGIN DESCRIPTION:
Elm 02 32
END DESCRIPTION:
DSS Export Rating Curves= 0
DSS Export Rating Curve Sorted= 0
DSS Export Volume Flow Curves= 0
DXF OffsetX= 0
DXF OffsetY= 0
DXF ScaleX= 1
DXF ScaleY= 10

--- Elm 02 32.p01 (plan) ---

Plan Title=Multiple Run
Short Identifier=Multiple
Geom File=g01
Flow File=f01
Subcritical Flow
K Sum by GR= 0
Std Step Tol= 0.01
Critical Tol= 0.01
Num of Std Step Trials= 20
Max Error Tol= 0.3
Flow Tol Ratio= 0.001
Split Flow NTrial= 30
Split Flow Tol= 0.02
Split Flow Ratio= 0.02
Log Output Level= 0
Friction Slope Method= 1
Unsteady Friction Slope Method= 2
Unsteady Bridges Friction Slope Method= 1
Parabolic Critical Depth
Global Vel Dist=  1 , 1 , 1
Global Log Level= 0
CheckData=True
Encroach Param= -1, 0, 0, 0
BEGIN DESCRIPTION:
Multiple Run
END DESCRIPTION:

--- Elm 02 32.f01 (steady flow) ---

Flow Title=Multiple
Number of Profiles=7
Profile Names=10-year,25-year,50-year,1pct_min,100-year,1pct_plu,500-year
River Rch & RM= Elm 02 32,Reach-1,9830
     164     221     267     200     320     440     466
River Rch & RM= Elm 02 32,Reach-1,3577
     228     313     383     290     465     640     695
Boundary for River Rch & Prof#=Elm 02 32,Reach-1,1
Up Type=0
Dn Type=3
Dn Slope=0.001
Boundary for River Rch & Prof#=Elm 02 32,Reach-1,2
Up Type=0
Dn Type=3
Dn Slope=0.001
Boundary for River Rch & Prof#=Elm 02 32,Reach-1,3
Up Type=0
Dn Type=3
Dn Slope=0.001
Boundary for River Rch & Prof#=Elm 02 32,Reach-1,4
Up Type=0
Dn Type=3
Dn Slope=0.001
Boundary for River Rch & Prof#=Elm 02 32,Reach-1,5
Up Type=0
Dn Type=3
Dn Slope=0.001
Boundary for River Rch & Prof#=Elm 02 32,Reach-1,6
Up Type=0
Dn Type=3
Dn Slope=0.001
Boundary for River Rch & Prof#=Elm 02 32,Reach-1,7
Up Type=0
Dn Type=3
Dn Slope=0.001

--- Elm 02 32.g01 (geometry) ---

Geom Title=Existing Conditions
Program Version=4.10

River Reach=Elm 02 32       ,Reach-1
Reach XY= 30
        1605605.        6864688.      1604557.45      6865532.54
      1604056.45      6865541.53      1603855.11      6865780.69
      1603668.43      6865701.63      1603647.24      6865431.83
      1603328.18      6865211.71      1603149.56       6864943.1
      1603004.99      6864980.47      1602871.25      6864905.13
      1602896.96      6864734.68      1602794.51      6864588.49
       1602327.7      6864814.09      1602347.21      6865041.42
       1602203.5      6865184.54      1601955.01      6865095.53
      1601589.66      6865238.05      1601405.01      6865145.53
        1601155.      6865230.44      1601015.48      6865188.94
      1600830.42      6865488.42      1600606.46      6865484.46
      1600349.07      6865290.24      1600098.79       6865280.2
      1599947.18      6864931.81      1599749.14      6864740.05
      1598984.82      6864838.28      1598715.83      6864788.46
      1598539.62      6864988.16        1598455.        6864888.

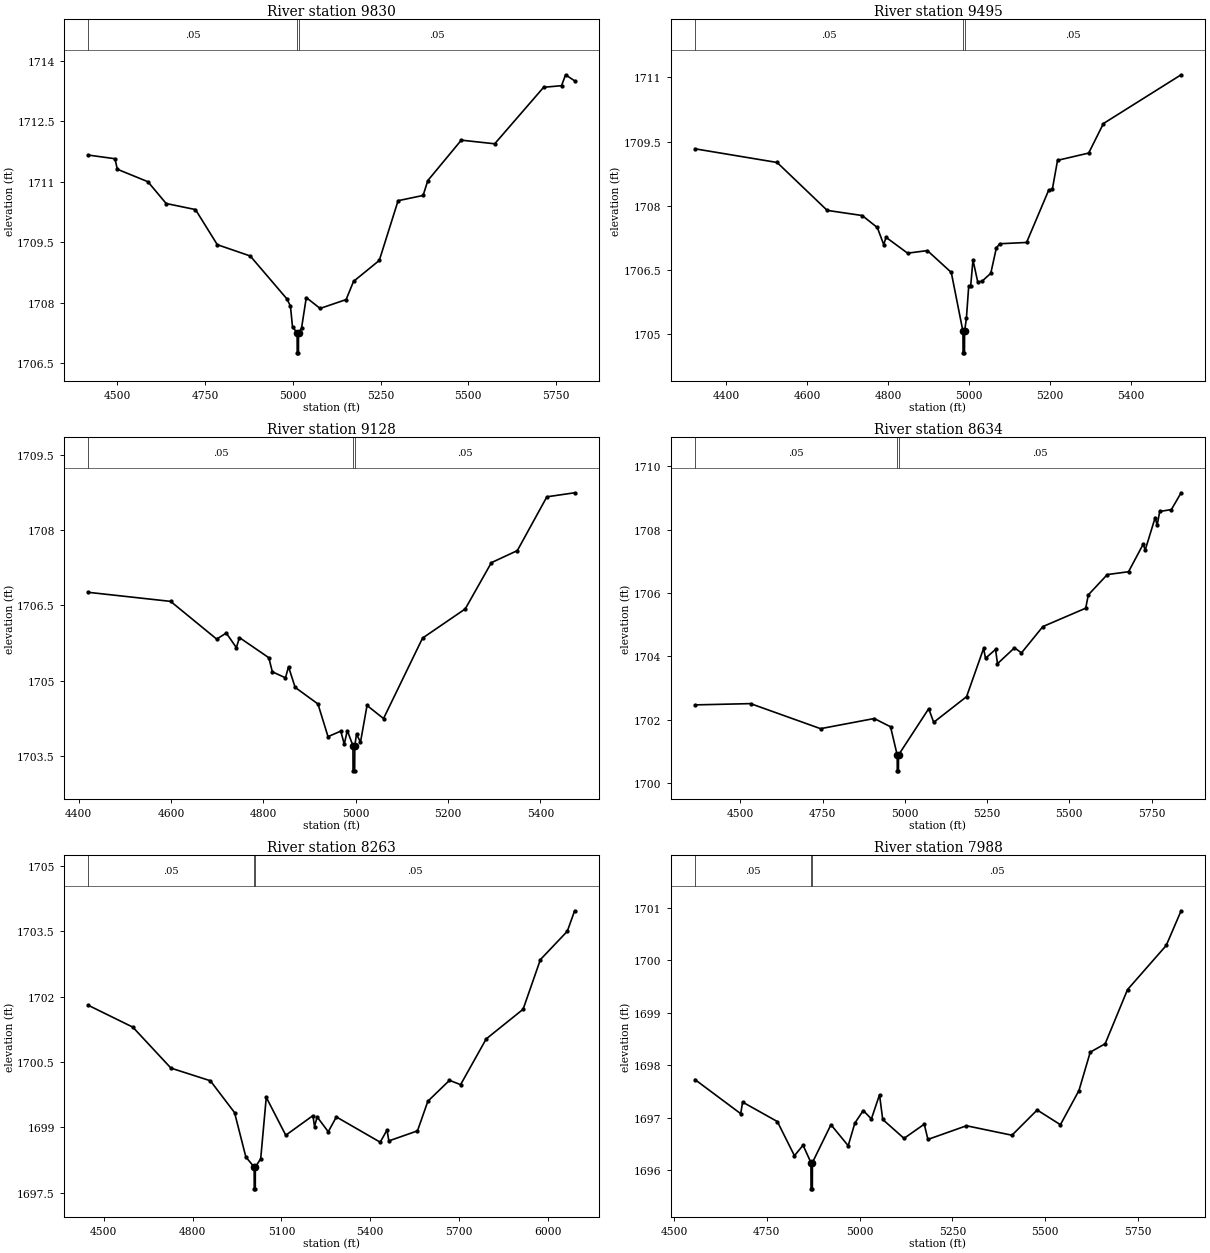
Type RM Length L Ch R = 1 ,9830    ,335,335,335
BEGIN DESCRIPTION:
Elm 02 32 9465.644
END DESCRIPTION:
XS GIS Cut Line= 3
      1605366.83      6864155.27       1605528.2      6864714.35
      1605789.92      6865473.19
#Sta/Elev= 30
  4418.1 1711.66  4493.8 1711.57  4500.3 1711.31  4587.5    1711  4639.5 1710.46
    4723 1710.31  4785.1 1709.44  4878.9 1709.16    4983  1708.1  4993.4 1707.92
  4999.3  1707.4  5012.4 1707.26  5012.7 1706.76  5016.2 1706.76  5016.4 1707.26
    5025 1707.37  5038.5 1708.13  5077.9 1707.86    5152 1708.08  5173.1 1708.53
  5246.4 1709.05    5300 1710.53  5371.2 1710.66  5384.7 1711.03  5479.9 1712.03
  5575.1 1711.94  5714.4 1713.34  5765.5 1713.38  5776.8 1713.65  5802.7  1713.5
#Mann= 3 ,-1 , 0
  4418.1     .05       0  5012.4    .035       0  5016.4     .05       0
Bank Sta=5012.4,5016.4
XS Rating Curve= 0 ,0
Exp/Cntr=0.3,0.1

Type RM Length L Ch R = 1 ,9495    ,367,367,367
BEGIN DESCRIPTION:
Elm 02 32 9494.62
END DESCRIPTION:
XS GIS Cut Line= 3
      1604986.28      6864381.66      1605324.82      6864972.81
      1605540.49      6865445.73
#Sta/Elev= 30
  4322.3 1709.33  4525.4 1709.01  4649.1 1707.89  4735.5 1707.77  4772.9 1707.49
  4788.7 1707.09  4794.5 1707.26  4847.7 1706.89  4896.6 1706.95  4955.6 1706.44
  4984.5 1705.06  4984.7 1704.56  4988.2 1704.56  4988.5 1705.06    4993 1705.37
  4998.7 1706.12  5003.5 1706.12  5009.2 1706.73  5020.9 1706.22  5031.2 1706.23
  5053.2 1706.42  5066.9 1707.01  5075.2 1707.11  5141.6 1707.14  5196.1 1708.36
  5205.2 1708.38  5218.1 1709.06    5295 1709.23  5331.4 1709.92  5523.3 1711.06
#Mann= 3 ,-1 , 0
  4322.3     .05       0  4984.5    .035       0  4988.5     .05       0
Bank Sta=4984.5,4988.5
XS Rating Curve= 0 ,0
Exp/Cntr=0.3,0.1

Type RM Length L Ch R = 1 ,9128    ,494,494,494
BEGIN DESCRIPTION:
Elm 02 32 9127.72
END DESCRIPTION:
XS GIS Cut Line= 3
      1604625.62      6864695.93      1605007.55      6865134.27
      1605328.74      6865479.33
#Sta/Elev= 30
  4421.4 1706.76  4599.4 1706.58  4699.1 1705.83  4719.9 1705.95  4741.8 1705.66
  4748.4 1705.86    4812 1705.46  4819.6 1705.18  4848.1 1705.06  4854.7 1705.28
    4869 1704.87  4918.4 1704.54  4940.2 1703.89  4967.9    1704  4975.3 1703.74
    4982 1704.01  4994.2 1703.71  4994.4 1703.21  4997.9 1703.21  4998.2 1703.71
  5001.9 1703.94  5010.5 1703.78  5024.7 1704.51  5060.4 1704.25  5144.9 1705.85
  5237.3 1706.43  5293.9 1707.35  5350.1 1707.59  5414.1 1708.66  5474.2 1708.74
#Mann= 3 ,-1 , 0
  4421.4     .05       0  4994.2    .035       0  4998.2     .05       0
Bank Sta=4994.2,4998.2
XS Rating Curve= 0 ,0
Exp/Cntr=0.3,0.1

Type RM Length L Ch R = 1 ,8634    ,371,371,371
BEGIN DESCRIPTION:
Elm 02 32 8633.88
END DESCRIPTION:
XS GIS Cut Line= 3
      1604239.29      6864956.28      1604640.79      6865453.28
        1605350.      6865903.02
#Sta/Elev= 30
  4361.3 1702.47  4530.6 1702.51  4743.5 1701.72  4906.7 1702.04  4956.3 1701.78
  4976.6 1700.89  4976.8 1700.39  4980.3 1700.39  4980.6 1700.89  5072.4 1702.35
  5087.6 1701.92  5187.6 1702.73  5239.3 1704.25  5245.2 1703.94  5275.7 1704.22
  5281.6 1703.77  5333.3 1704.27  5354.5 1704.11  5419.6 1704.94  5549.9 1705.52
  5557.8 1705.94  5615.5 1706.58  5680.1 1706.67  5724.8 1707.54  5730.7 1707.35
  5761.2 1708.38  5767.1 1708.13  5774.9 1708.57  5810.4 1708.63    5840 1709.16
#Mann= 3 ,-1 , 0
  4361.3     .05       0  4976.6     .05       0  4980.6     .05       0
Bank Sta=4976.6,4980.6
XS Rating Curve= 0 ,0
Exp/Cntr=0.3,0.1

Type RM Length L Ch R = 1 ,8263    ,275,275,275
BEGIN DESCRIPTION:
Mapping XS df3a2141
END DESCRIPTION:
XS GIS Cut Line= 5
      1604207.02      6864995.98      1604296.53       6865391.7
      1604304.68       6865590.6      1604417.52      6865707.79
      1604849.38      6866469.51
#Sta/Elev= 30
  4447.9  1701.8    4598  1701.3  4726.8 1700.36  4859.9 1700.07  4941.7 1699.34
    4980 1698.32    5008 1698.09  5008.3 1697.59  5011.8 1697.59    5012 1698.09
  5030.1 1698.28  5048.9 1699.69  5114.8 1698.82  5206.6 1699.27    5212 1699.02
  5220.9 1699.24  5258.4  1698.9  5285.8 1699.24    5434 1698.66    5457 1698.94
  5463.2 1698.69  5559.9 1698.92    5595  1699.6  5668.1 1700.08  5705.6 1699.98
  5792.1 1701.03  5916.8 1701.71  5975.3 1702.85  6066.2  1703.5    6091 1703.97
#Mann= 3 ,-1 , 0
  4447.9     .05       0    5008     .07       0    5012     .05       0
Bank Sta=5008,5012
XS Rating Curve= 0 ,0
Exp/Cntr=0.3,0.1

Type RM Length L Ch R = 1 ,7988    ,840,840,840
BEGIN DESCRIPTION:
Mapping XS fb1cc88d
END DESCRIPTION:
XS GIS Cut Line= 4
      1603937.15      6865131.28       1603965.8      6865407.33
      1604179.34      6865886.49      1604223.61      6866391.74
#Sta/Elev= 30
  4556.4 1697.73  4679.8 1697.08  4684.9  1697.3  4778.5 1696.93  4824.5 1696.28
  4847.7 1696.48  4868.9 1696.15  4869.2 1695.65  4872.7 1695.65  4872.9 1696.15
  4922.8 1696.87  4969.3 1696.47  4987.1  1696.9  5009.8 1697.14  5031.7 1696.98
  5053.6 1697.44  5062.2 1696.97  5119.6 1696.61  5174.1 1696.88  5183.9 1696.59
  5287.7 1696.85  5410.2 1696.67  5478.1 1697.15  5540.7 1696.87  5590.6 1697.52
    5621 1698.25  5661.2 1698.41  5721.4 1699.44  5825.6 1700.28  5865.7 1700.94
#Mann= 3 ,-1 , 0
  4556.4     .05       0  4868.9     .07       0  4872.9     .05       0
Bank Sta=4868.9,4872.9
XS Rating Curve= 0 ,0
Exp/Cntr=0.3,0.1

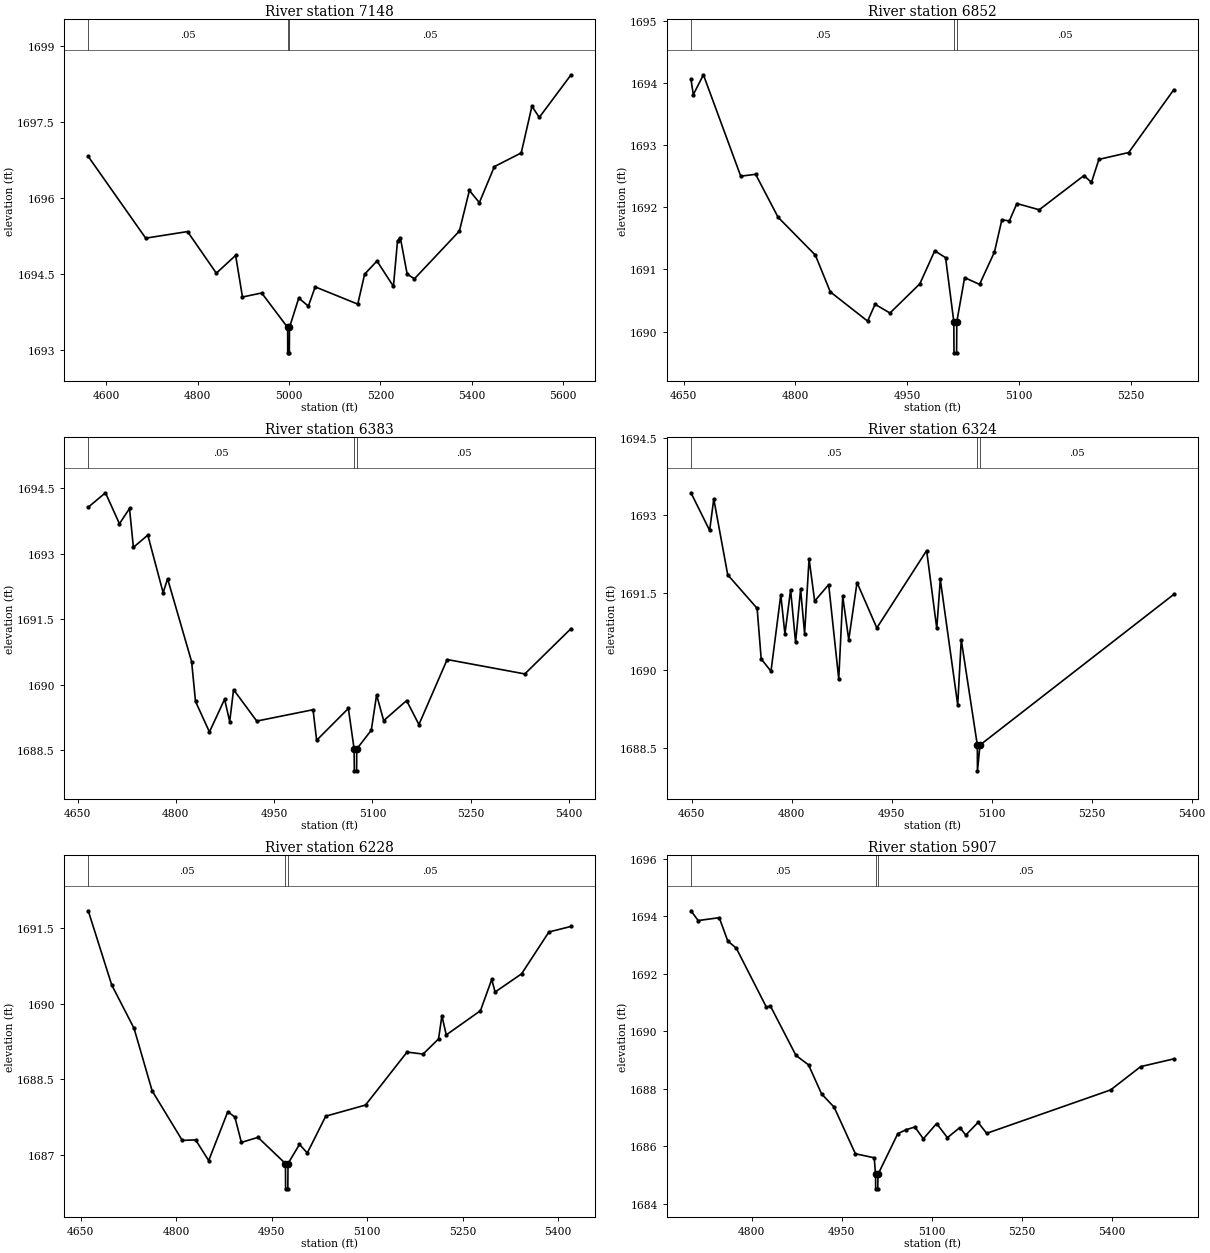
Type RM Length L Ch R = 1 ,7148    ,296,296,296
BEGIN DESCRIPTION:
Mapping XS 30e889b9
END DESCRIPTION:
XS GIS Cut Line= 4
      1603817.34      6865016.74      1603710.59      6865279.72
      1603478.82      6865626.08      1603335.59      6865951.59
#Sta/Elev= 30
  4560.8 1696.82  4686.5 1695.21    4778 1695.34    4841 1694.52  4883.2 1694.87
  4898.2 1694.05  4940.2 1694.13    4997 1693.45  4997.2 1692.95  5000.7 1692.95
    5001 1693.45  5021.3 1694.03  5042.3 1693.87  5057.3 1694.25  5150.4 1693.91
  5165.4  1694.5  5192.4 1694.76  5228.4 1694.26  5237.4 1695.16  5243.5 1695.22
  5258.5  1694.5  5274.4 1694.41  5372.7 1695.35  5394.6 1696.15  5416.4 1695.91
  5449.2 1696.62    5508 1696.89  5531.4 1697.81  5547.5 1697.59    5617 1698.43
#Mann= 3 ,-1 , 0
  4560.8     .05       0    4997     .05       0    5001     .05       0
Bank Sta=4997,5001
XS Rating Curve= 0 ,0
Exp/Cntr=0.3,0.1

Type RM Length L Ch R = 1 ,6852    ,469,469,469
BEGIN DESCRIPTION:
Elm 02 32 6851.85
END DESCRIPTION:
XS GIS Cut Line= 3
      1603410.26      6864901.31      1603390.73      6865242.44
      1603376.41      6865548.41
#Sta/Elev= 30
  4659.9 1694.06    4663 1693.81  4676.6 1694.13  4726.7  1692.5  4746.7 1692.53
  4776.8 1691.84  4826.9 1691.23  4846.9 1690.64    4897 1690.17    4907 1690.44
    4927  1690.3  4967.1 1690.77  4987.1  1691.3  5001.6 1691.19  5012.7 1690.16
  5012.9 1689.66  5016.4 1689.66  5016.7 1690.16  5027.2 1690.87  5047.2 1690.76
  5067.2 1691.28  5077.2  1691.8  5087.2 1691.78  5097.3 1692.06  5127.3 1691.96
  5187.4 1692.51  5197.4  1692.4  5207.4 1692.77  5247.4 1692.88  5307.9 1693.89
#Mann= 3 ,-1 , 0
  4659.9     .05       0  5012.7     .05       0  5016.7     .05       0
Bank Sta=5012.7,5016.7
XS Rating Curve= 0 ,0
Exp/Cntr=0.3,0.1

Type RM Length L Ch R = 1 ,6383    ,59,59,59
BEGIN DESCRIPTION:
Elm 02 32 6382.8
END DESCRIPTION:
XS GIS Cut Line= 4
      1603312.55       6864729.4      1603092.31      6864863.93
      1603084.72      6864939.88       1603234.2      6865313.59
#Sta/Elev= 30
  4666.3 1694.07  4692.6  1694.4  4713.9 1693.69  4729.3 1694.04  4735.2 1693.15
  4757.2 1693.43  4780.6 1692.11  4787.4 1692.43  4824.1 1690.53    4830 1689.62
  4851.3 1688.92  4874.4 1689.67  4882.2 1689.16  4888.1 1689.89  4923.5 1689.17
  5009.4 1689.43  5014.9 1688.73  5063.3 1689.46  5072.1 1688.53  5072.4 1688.03
  5075.9 1688.03  5076.1 1688.53  5098.3 1688.96  5106.4 1689.77  5117.2 1689.18
  5152.2 1689.64    5171 1689.09  5214.1 1690.58  5332.6 1690.25  5403.2 1691.29
#Mann= 3 ,-1 , 0
  4666.3     .05       0  5072.1     .05       0  5076.1     .05       0
Bank Sta=5072.1,5076.1
XS Rating Curve= 0 ,0
Exp/Cntr=0.3,0.1

Type RM Length L Ch R = 1 ,6324    ,96,96,96
BEGIN DESCRIPTION:
Elm 02 32 6324.25
END DESCRIPTION:
XS GIS Cut Line= 5
      1603169.36      6864664.27      1603077.12      6864791.23
      1603008.76      6864894.31      1603033.72      6864962.67
      1603152.87      6865313.61
#Sta/Elev= 30
  4649.1 1693.44  4677.1 1692.71  4683.3 1693.32  4704.2 1691.85  4748.3  1691.2
  4754.4 1690.22  4769.1 1689.98  4783.8 1691.46    4790  1690.7  4798.5 1691.56
    4806 1690.54  4813.5 1691.57  4819.5 1690.71  4826.2 1692.16  4834.6 1691.34
  4855.6 1691.66  4870.7 1689.83  4876.7 1691.43  4885.7 1690.59  4898.1  1691.7
  4927.8 1690.82  5002.5 1692.32  5017.7 1690.81    5023 1691.76  5049.1 1689.33
  5054.4 1690.59  5078.5 1688.55  5078.7 1688.05  5082.5 1688.55  5373.1 1691.47
#Mann= 3 ,-1 , 0
  4649.1     .05       0  5078.5     .05       0  5082.5     .05       0
Bank Sta=5078.5,5082.5
XS Rating Curve= 0 ,0
Exp/Cntr=0.3,0.1

Type RM Length L Ch R = 1 ,6228    ,321,321,321
BEGIN DESCRIPTION:
Elm 02 32 6227.76
END DESCRIPTION:
XS GIS Cut Line= 6
      1603084.71      6864645.84      1602987.06      6864759.76
       1602955.6      6864892.14       1602955.6      6864947.48
      1603002.25       6865105.9      1603095.58      6865340.31
#Sta/Elev= 30
  4661.7 1691.84  4698.6 1690.37  4733.7 1689.51  4762.2 1688.27  4809.5 1687.29
  4830.5  1687.3    4851 1686.89  4881.1 1687.86  4892.2 1687.75  4902.4 1687.25
  4928.5 1687.35  4971.7 1686.83  4971.9 1686.33  4975.4 1686.33  4975.7 1686.83
  4993.7 1687.21    5006 1687.04    5035 1687.77  5097.5 1687.99  5162.8 1689.04
    5188    1689  5212.3  1689.3  5217.6 1689.76  5224.4 1689.38  5278.2 1689.86
  5295.9 1690.48  5301.2 1690.23  5342.8 1690.59  5385.8 1691.42  5420.6 1691.53
#Mann= 3 ,-1 , 0
  4661.7     .05       0  4971.7     .05       0  4975.7     .05       0
Bank Sta=4971.7,4975.7
XS Rating Curve= 0 ,0
Exp/Cntr=0.3,0.1

Type RM Length L Ch R = 1 ,5907    ,308,308,308
BEGIN DESCRIPTION:
Elm 02 32 5907.14
END DESCRIPTION:
XS GIS Cut Line= 5
      1603098.83      6864504.92      1602873.44      6864707.31
      1602797.49      6864777.84      1602775.05       6864884.6
      1602779.83       6865173.2
#Sta/Elev= 30
  4698.9 1694.19  4710.9 1693.85    4746 1693.95  4760.2 1693.14  4774.4 1692.89
  4824.5 1690.84  4831.2 1690.88  4873.8 1689.16  4894.8 1688.83  4916.5 1687.82
  4937.4 1687.36  4972.8 1685.74  5004.2  1685.6  5006.4 1685.02  5006.6 1684.52
  5010.1 1684.52  5010.4 1685.02  5043.5 1686.44  5057.7 1686.58  5071.9 1686.67
    5086 1686.26  5108.1 1686.79  5126.1  1686.3  5146.7 1686.65  5156.7 1686.39
  5177.2 1686.83  5191.5 1686.45    5398 1687.96    5448 1688.77  5503.2 1689.04
#Mann= 3 ,-1 , 0
  4698.9     .05       0  5006.4     .03       0  5010.4     .05       0
Bank Sta=5006.4,5010.4
XS Rating Curve= 0 ,0
Exp/Cntr=0.3,0.1

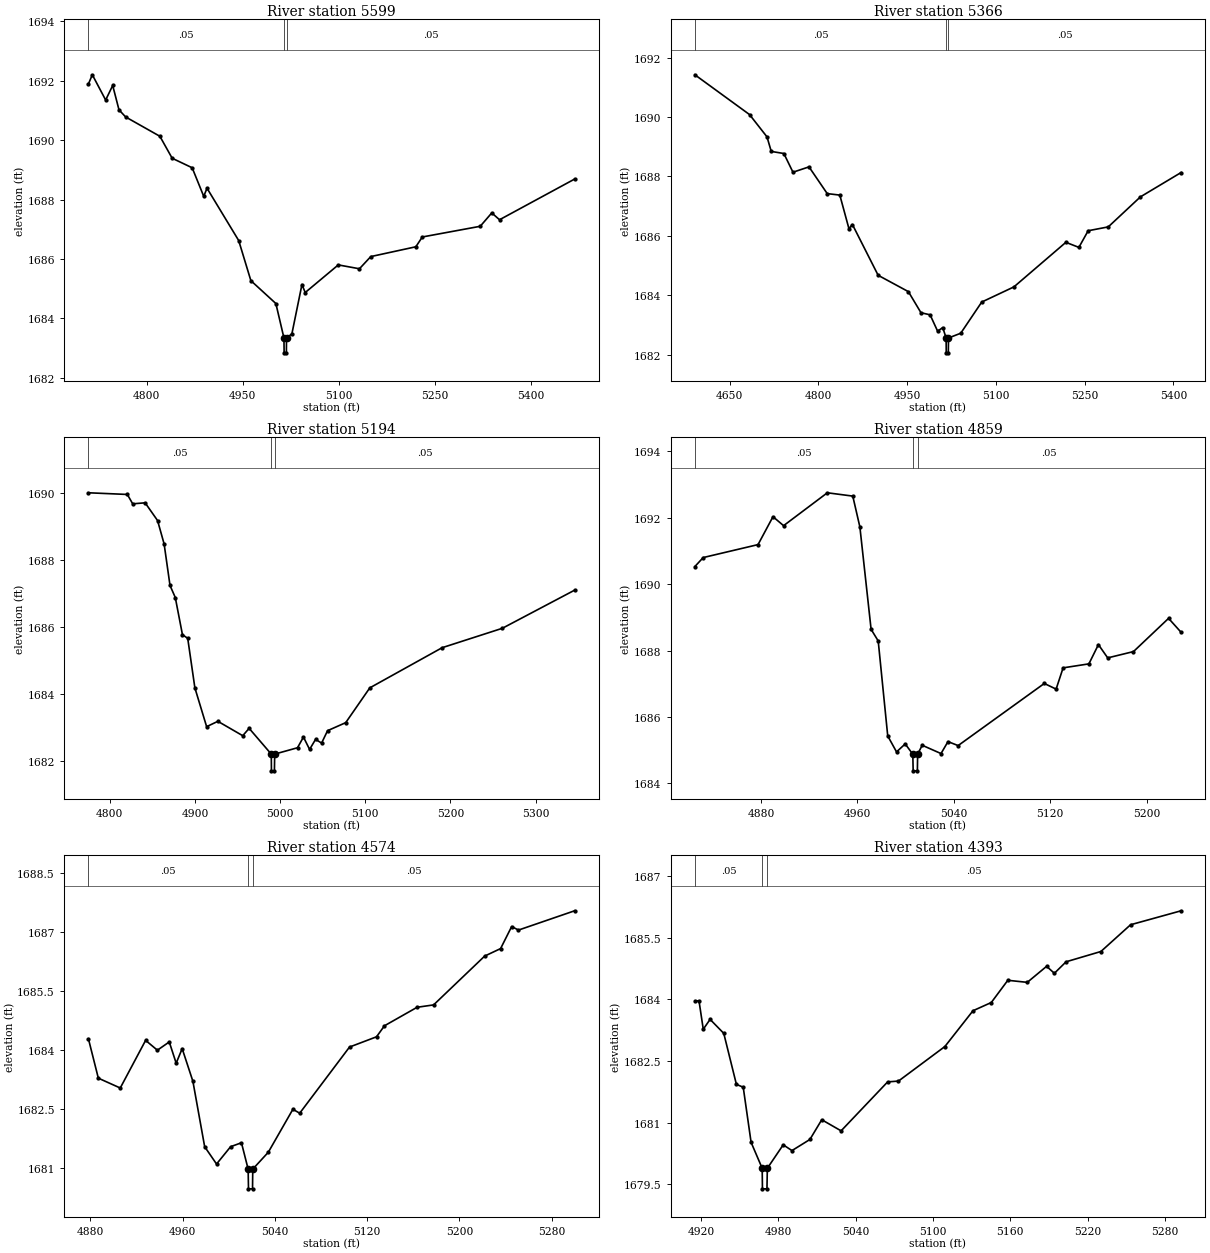
Type RM Length L Ch R = 1 ,5599    ,233,233,233
BEGIN DESCRIPTION:
Elm 02 32 5598.34
END DESCRIPTION:
XS GIS Cut Line= 4
      1602591.03      6864392.08      1602669.81      6864674.67
      1602698.75       6864784.5      1602731.92      6865134.69
#Sta/Elev= 30
  4709.2 1691.89  4715.3  1692.2  4736.1 1691.35  4747.1 1691.84  4756.9 1691.02
  4767.3 1690.78  4820.7 1690.13  4839.9 1689.39  4871.1 1689.07  4889.1 1688.11
  4894.3 1688.38  4943.7 1686.62  4962.7 1685.27  5001.7  1684.5  5014.3 1683.34
  5014.6 1682.84  5018.1 1682.84  5018.3 1683.34  5026.7 1683.48  5042.4 1685.14
  5047.5 1684.87  5099.1  1685.8  5132.1 1685.67  5149.8 1686.08  5220.1 1686.41
  5230.2 1686.74  5320.6  1687.1  5338.6 1687.55  5350.7 1687.32  5467.9 1688.69
#Mann= 3 ,-1 , 0
  4709.2     .05       0  5014.3     .03       0  5018.3     .05       0
Bank Sta=5014.3,5018.3
XS Rating Curve= 0 ,0
Exp/Cntr=0.3,0.1

Type RM Length L Ch R = 1 ,5366    ,172,172,172
BEGIN DESCRIPTION:
Elm 02 32 5365.5
END DESCRIPTION:
XS GIS Cut Line= 3
      1602241.62      6864394.22      1602457.14      6864744.11
      1602650.89      6865106.53
#Sta/Elev= 30
  4591.2 1691.42  4683.6 1690.08  4713.1 1689.33  4720.3 1688.84  4741.6 1688.77
    4757 1688.14  4784.1 1688.32  4814.9 1687.42  4836.2 1687.37  4851.6 1686.24
  4857.5 1686.38    4901 1684.67  4952.1 1684.12  4973.4 1683.41  4988.8 1683.34
  5001.5 1682.79  5010.2 1682.91  5015.9 1682.56  5016.1 1682.06  5019.6 1682.06
  5019.9 1682.56  5040.6 1682.72  5076.1 1683.77  5130.5 1684.28  5218.3 1685.78
  5240.3 1685.61    5256 1686.17    5290  1686.3  5344.3 1687.31  5413.1 1688.13
#Mann= 3 ,-1 , 0
  4591.2     .05       0  5015.9     .03       0  5019.9     .05       0
Bank Sta=5015.9,5019.9
XS Rating Curve= 0 ,0
Exp/Cntr=0.3,0.1

Type RM Length L Ch R = 1 ,5194    ,335,335,335
BEGIN DESCRIPTION:
Elm 02 32 5193.66
END DESCRIPTION:
XS GIS Cut Line= 3
      1602133.79      6864695.29      1602313.91      6864829.83
      1602555.89      6865077.25
#Sta/Elev= 30
    4775 1690.01  4820.7 1689.96    4827 1689.68  4841.6 1689.71  4856.2 1689.18
  4863.9 1688.48  4870.8 1687.24    4877 1686.88  4885.4 1685.77  4891.6 1685.66
    4900 1684.18  4913.8 1683.02    4927 1683.18  4956.2 1682.75  4963.7 1682.97
  4989.7  1682.2  4989.9  1681.7  4993.4  1681.7  4993.7  1682.2  5020.5 1682.39
  5027.5 1682.71  5034.7 1682.34  5041.7 1682.64  5048.8 1682.53  5055.8  1682.9
  5077.1 1683.14  5105.4 1684.18  5190.3 1685.38    5261 1685.96  5345.9  1687.1
#Mann= 3 ,-1 , 0
    4775     .05       0  4989.7     .05       0  4993.7     .05       0
Bank Sta=4989.7,4993.7
XS Rating Curve= 0 ,0
Exp/Cntr=0.3,0.1

Type RM Length L Ch R = 1 ,4859    ,285,285,285
BEGIN DESCRIPTION:
Elm 02 32 4858.59
END DESCRIPTION:
XS GIS Cut Line= 3
      1602178.58      6864973.58      1602273.18      6865120.26
      1602390.17      6865316.96
#Sta/Elev= 30
  4825.2 1690.53  4832.1  1690.8  4877.6 1691.19    4890 1692.03  4898.8 1691.76
  4935.1 1692.75  4956.2 1692.65  4962.1 1691.72  4971.4 1688.64  4977.3 1688.29
  4985.2 1685.43  4992.5 1684.95  4999.7 1685.19    5006 1684.88  5006.3 1684.38
  5009.8 1684.38    5010 1684.88  5013.8 1685.15  5029.4  1684.9  5035.2 1685.26
  5043.6 1685.14  5115.1 1687.01  5124.9 1686.84  5130.7 1687.48  5152.1  1687.6
    5160 1688.18  5167.7 1687.78  5189.1 1687.97  5218.2 1688.97  5228.6 1688.55
#Mann= 3 ,-1 , 0
  4825.2     .05       0    5006     .05       0    5010     .05       0
Bank Sta=5006,5010
XS Rating Curve= 0 ,0
Exp/Cntr=0.3,0.1

Type RM Length L Ch R = 1 ,4574    ,181,181,181
BEGIN DESCRIPTION:
Elm 02 32 4574.26
END DESCRIPTION:
XS GIS Cut Line= 3
      1602003.22       6865019.6      1602030.13      6865140.22
      1602185.35      6865394.62
#Sta/Elev= 30
  4878.3 1684.28  4886.9 1683.28  4905.9 1683.03  4927.9 1684.24  4938.1 1683.99
  4948.4  1684.2  4954.4 1683.66  4959.6 1684.03  4968.9  1683.2  4979.1 1681.54
  4989.4  1681.1  5001.6 1681.54    5011 1681.64  5016.8 1680.97  5017.1 1680.47
  5020.6 1680.47  5020.8 1680.97  5034.3  1681.4  5055.6 1682.49  5061.5 1682.39
  5104.7 1684.07  5128.1 1684.33    5135 1684.61  5163.3 1685.08  5177.6 1685.14
  5221.9 1686.38  5235.7 1686.57  5245.3 1687.13  5251.2 1687.04  5299.9 1687.53
#Mann= 3 ,-1 , 0
  4878.3     .05       0  5016.8     .05       0  5020.8     .05       0
Bank Sta=5016.8,5020.8
XS Rating Curve= 0 ,0
Exp/Cntr=0.3,0.1

Type RM Length L Ch R = 1 ,4393    ,169,169,169
BEGIN DESCRIPTION:
Elm 02 32 4393.45
END DESCRIPTION:
XS GIS Cut Line= 3
      1601847.84       6865056.9      1601876.48      6865138.49
      1602037.09      6865380.71
#Sta/Elev= 30
  4915.4 1683.96  4918.6 1683.96  4921.9 1683.27  4927.2 1683.51  4937.8 1683.17
  4947.6 1681.93  4952.9 1681.86    4959 1680.52  4967.6 1679.89  4967.8 1679.39
  4971.3 1679.39  4971.6 1679.89  4983.9 1680.46  4990.7 1680.32  5004.6 1680.59
  5013.8 1681.07  5028.8  1680.8  5064.9 1681.99  5073.3 1682.01  5109.3 1682.85
  5131.1 1683.72  5145.3 1683.92  5158.1 1684.46  5173.2 1684.41  5188.2  1684.8
  5194.2 1684.63  5203.3 1684.91  5230.3 1685.16  5253.3 1685.81  5292.5 1686.15
#Mann= 3 ,-1 , 0
  4915.4     .05       0  4967.6     .05       0  4971.6     .05       0
Bank Sta=4967.6,4971.6
XS Rating Curve= 0 ,0
Exp/Cntr=0.3,0.1

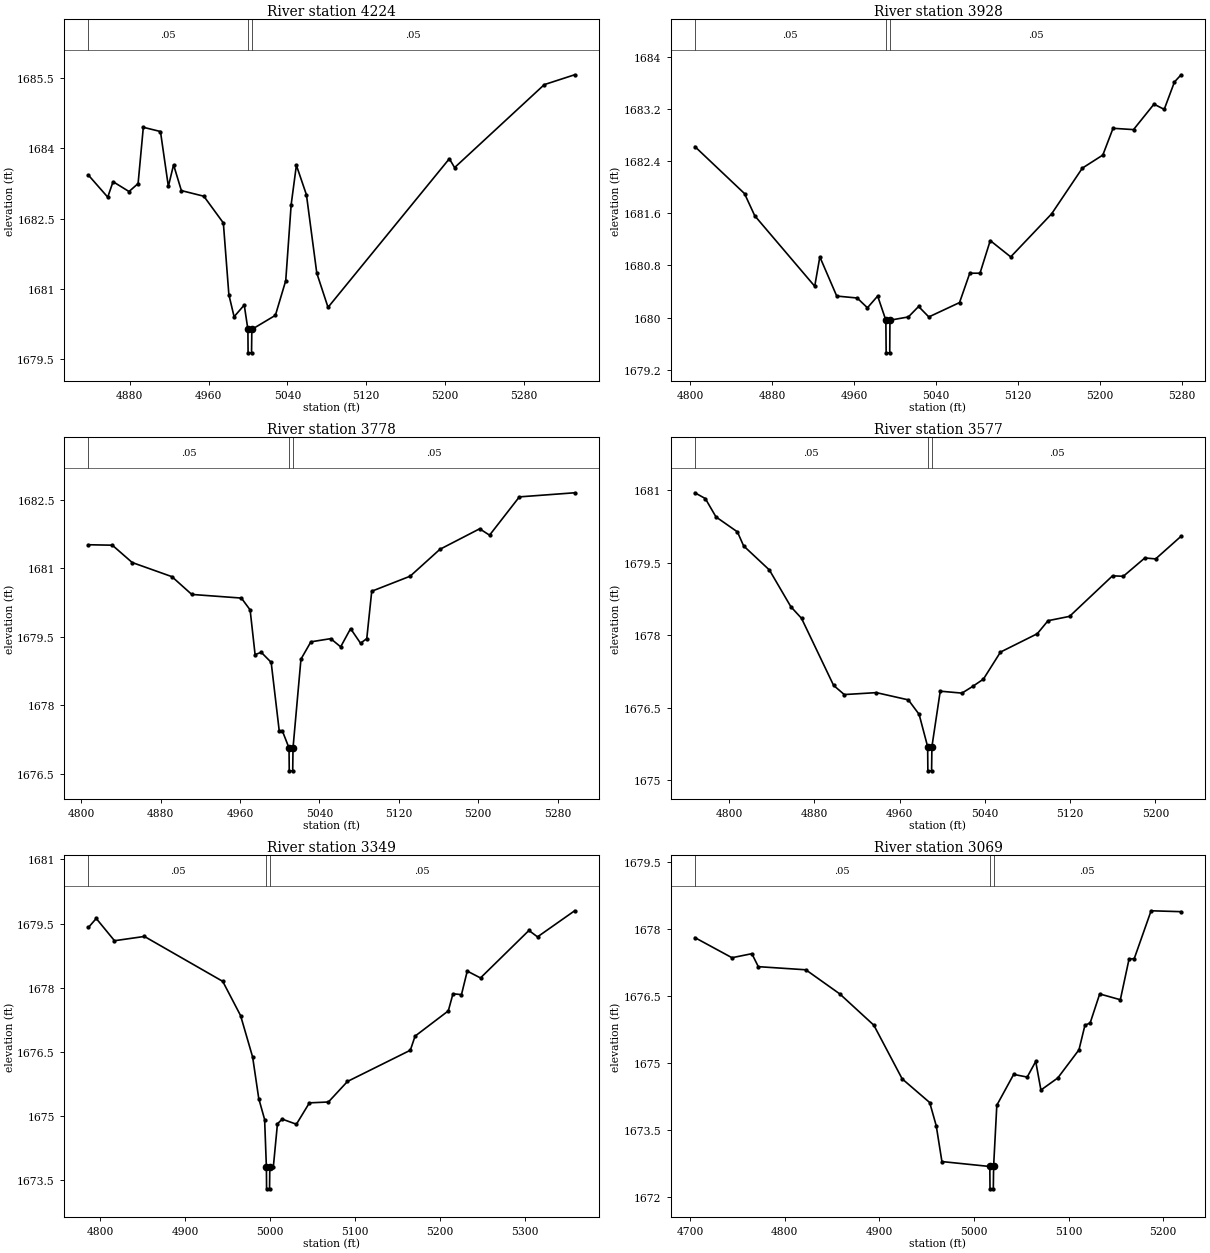
Type RM Length L Ch R = 1 ,4224    ,296,296,296
BEGIN DESCRIPTION:
Elm 02 32 4223.75
END DESCRIPTION:
XS GIS Cut Line= 3
      1601651.67      6864989.22      1601707.21      6865143.69
       1601807.9      6865457.05
#Sta/Elev= 30
  4838.1 1683.43  4857.7 1682.96  4863.1 1683.29  4879.3 1683.08  4888.5 1683.25
  4893.8 1684.45  4911.2 1684.36  4919.2 1683.19  4924.5 1683.65  4932.4  1683.1
  4955.2 1682.98    4975 1682.41  4980.6 1680.88  4985.9 1680.41  4996.2 1680.66
  4999.9 1680.14  5000.1 1679.64  5003.6 1679.64  5003.9 1680.14  5027.8 1680.44
  5038.3 1681.18  5043.8  1682.8  5049.1 1683.64  5059.3 1683.01  5069.8 1681.34
  5081.2 1680.61  5204.3 1683.78  5209.6 1683.59  5300.6 1685.36  5331.4 1685.57
#Mann= 3 ,-1 , 0
  4838.1     .05       0  4999.9     .05       0  5003.9     .05       0
Bank Sta=4999.9,5003.9
XS Rating Curve= 0 ,0
Exp/Cntr=0.3,0.1

Type RM Length L Ch R = 1 ,3928    ,150,150,150
BEGIN DESCRIPTION:
Elm 02 32 3928.23
END DESCRIPTION:
XS GIS Cut Line= 3
       1601454.7      6864989.56      1601463.38      6865187.02
      1601465.54      6865464.46
#Sta/Elev= 30
  4804.4 1682.62  4852.9  1681.9  4862.9 1681.56  4921.5 1680.48  4926.5 1680.93
    4943 1680.33    4963  1680.3    4973 1680.15    4983 1680.33    4991 1679.96
  4991.3 1679.46  4994.8 1679.46    4995 1679.96    5013 1680.01    5023 1680.17
    5033 1680.01    5063 1680.23    5073 1680.68    5083 1680.68    5093 1681.18
    5113 1680.93    5153 1681.59    5183 1682.29    5203 1682.49    5213  1682.9
    5233 1682.88    5253 1683.27    5263 1683.19    5273 1683.61  5279.5 1683.72
#Mann= 3 ,-1 , 0
  4804.4     .05       0    4991     .05       0    4995     .05       0
Bank Sta=4991,4995
XS Rating Curve= 0 ,0
Exp/Cntr=0.3,0.1

Type RM Length L Ch R = 1 ,3778    ,201,201,201
BEGIN DESCRIPTION:
Elm 02 32 3777.98
END DESCRIPTION:
XS GIS Cut Line= 3
      1601341.85      6864993.91      1601339.68      6865189.19
      1601340.76       6865483.7
#Sta/Elev= 30
  4807.3 1681.52  4831.4 1681.51  4851.4 1681.13  4891.4 1680.82  4911.4 1680.43
  4961.4 1680.35  4970.2 1680.09  4975.2 1679.11  4981.4 1679.16  4991.4 1678.94
  4999.5 1677.44  5002.6 1677.44  5009.4 1677.06  5009.6 1676.56  5013.1 1676.56
  5013.4 1677.06  5021.4 1679.01  5031.4 1679.39  5051.4 1679.46  5061.4 1679.28
  5071.4 1679.68  5081.4 1679.36  5087.7 1679.46  5092.7  1680.5  5131.4 1680.83
  5161.4 1681.42  5201.4 1681.87  5211.4 1681.73  5241.4 1682.57  5297.1 1682.66
#Mann= 3 ,-1 , 0
  4807.3     .05       0  5009.4     .05       0  5013.4     .05       0
Bank Sta=5009.4,5013.4
XS Rating Curve= 0 ,0
Exp/Cntr=0.3,0.1

Type RM Length L Ch R = 1 ,3577    ,228,228,228
BEGIN DESCRIPTION:
Elm 02 32 3577.35
END DESCRIPTION:
XS GIS Cut Line= 3
      1601136.78      6864998.24      1601153.05      6865232.59
      1601182.34      6865451.73
#Sta/Elev= 30
  4768.1 1680.95  4777.9 1680.83  4787.9 1680.45    4808 1680.14  4813.8 1679.85
    4838 1679.35  4858.1 1678.59  4868.1 1678.35  4898.2 1676.96  4908.2 1676.77
  4938.3 1676.81  4968.3 1676.66  4978.4 1676.36  4986.4 1675.69  4986.6 1675.19
  4990.1 1675.19  4990.4 1675.69  4998.2 1676.84  5018.6  1676.8  5028.7 1676.94
  5038.7 1677.09  5054.7 1677.65  5089.2 1678.03  5099.3  1678.3  5119.5 1678.39
  5159.8 1679.23  5169.9 1679.22  5190.1  1679.6  5200.2 1679.58  5224.1 1680.05
#Mann= 3 ,-1 , 0
  4768.1     .05       0  4986.4     .05       0  4990.4     .05       0
Bank Sta=4986.4,4990.4
XS Rating Curve= 0 ,0
Exp/Cntr=0.3,0.1

Type RM Length L Ch R = 1 ,3349    ,280,280,280
BEGIN DESCRIPTION:
Elm 02 32 3348.59
END DESCRIPTION:
XS GIS Cut Line= 3
      1600807.97      6865081.74      1600955.57      6865236.93
      1601116.16      6865557.03
#Sta/Elev= 30
  4785.9 1679.41  4795.1 1679.62  4816.6  1679.1  4851.8  1679.2    4944 1678.15
    4965 1677.35  4979.2 1676.38  4986.4 1675.41  4993.3 1674.92  4995.4  1673.8
  4995.6  1673.3  4999.1  1673.3  4999.4  1673.8  5003.5  1673.8  5008.4 1674.82
    5014 1674.93  5030.7 1674.81    5046 1675.31  5068.4 1675.33  5090.8 1675.81
  5164.8 1676.54  5170.4 1676.87  5209.5 1677.46    5215 1677.86    5225 1677.84
  5231.8 1678.39  5247.4 1678.23  5304.4 1679.34  5314.5 1679.19  5358.2  1679.8
#Mann= 3 ,-1 , 0
  4785.9     .05       0  4995.4     .05       0  4999.4     .05       0
Bank Sta=4995.4,4999.4
XS Rating Curve= 0 ,0
Exp/Cntr=0.3,0.1

Type RM Length L Ch R = 1 ,3069    ,249,249,249
BEGIN DESCRIPTION:
Elm 02 32 3069.03
END DESCRIPTION:
XS GIS Cut Line= 3
      1600686.63      6865232.54      1600852.63      6865477.74
       1600940.8      6865676.66
#Sta/Elev= 30
  4705.1 1677.81  4744.3 1677.36  4765.3 1677.45  4772.1 1677.16  4822.3 1677.09
  4858.2 1676.55  4894.2 1675.85  4924.1 1674.65  4953.2 1674.12  4960.1  1673.6
  4966.1  1672.8  5016.7 1672.69  5016.9 1672.19  5020.4 1672.19  5020.7 1672.69
  5024.1 1674.06  5041.9 1674.75  5056.2 1674.69  5065.2 1675.04  5070.7  1674.4
  5088.5 1674.67  5110.9  1675.3  5117.2 1675.85  5122.7  1675.9  5132.8 1676.55
  5154.6 1676.42  5163.8 1677.33  5169.3 1677.34  5187.1 1678.41  5218.8 1678.39
#Mann= 3 ,-1 , 0
  4705.1     .05       0  5016.7     .03       0  5020.7     .05       0
Bank Sta=5016.7,5020.7
XS Rating Curve= 0 ,0
Exp/Cntr=0.3,0.1

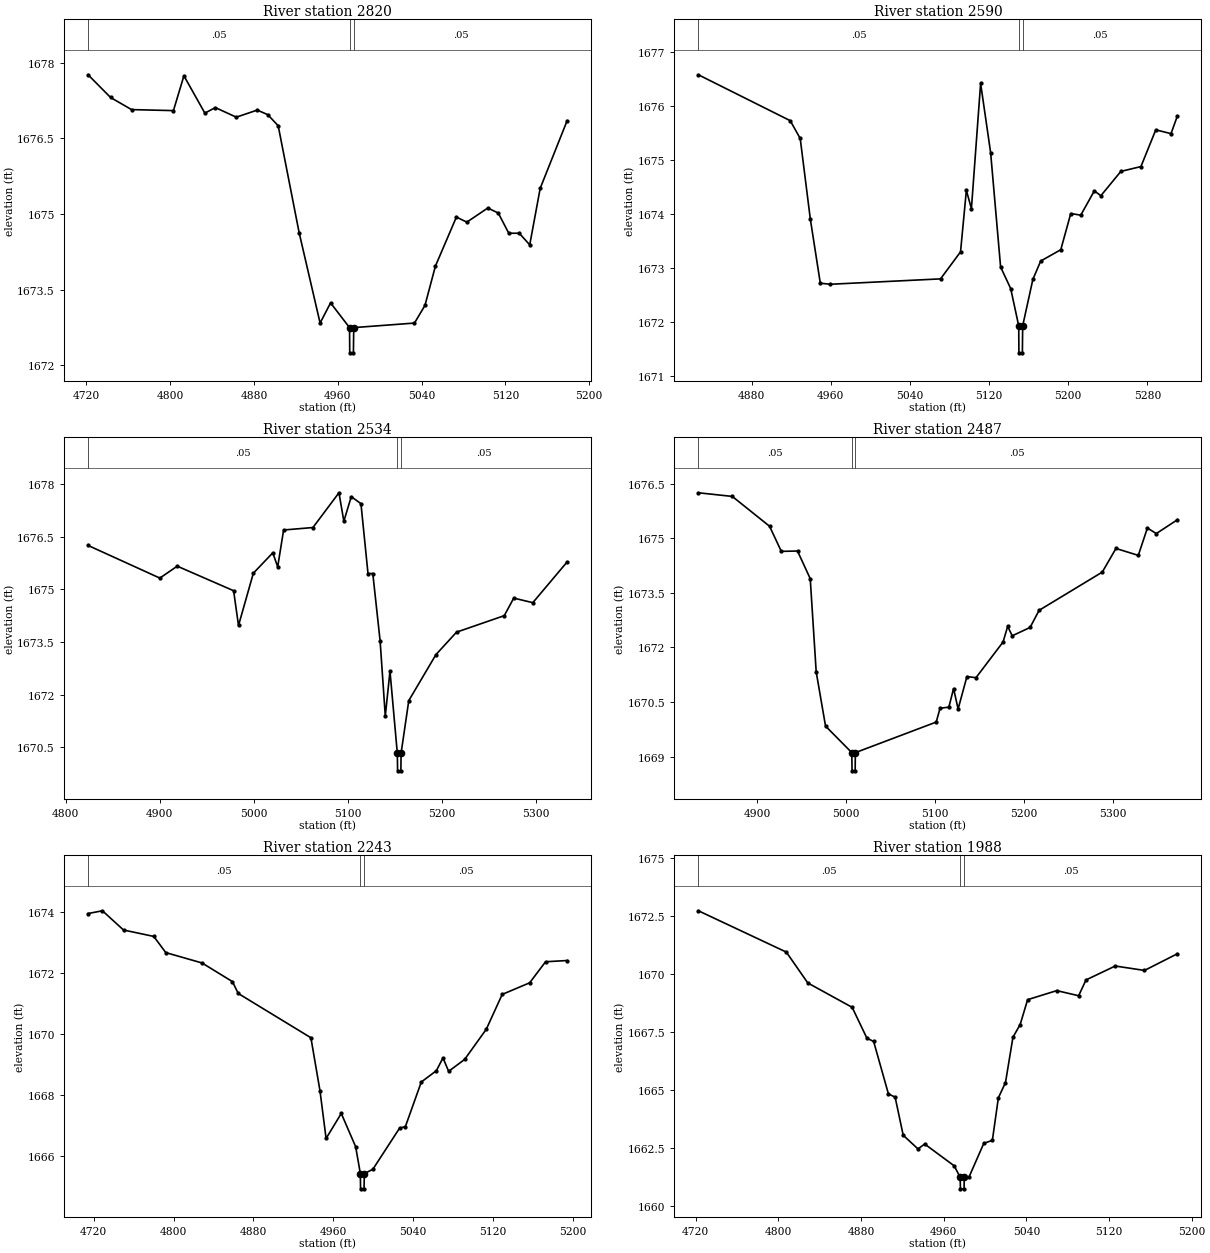
Type RM Length L Ch R = 1 ,2820    ,230,230,230
BEGIN DESCRIPTION:
Elm 02 32 2820.14
END DESCRIPTION:
XS GIS Cut Line= 3
      1600601.98      6865206.52      1600608.49      6865486.42
      1600605.25      6865663.71
#Sta/Elev= 30
  4721.7 1677.76  4743.2 1677.31  4763.2 1677.07  4803.2 1677.05  4813.2 1677.74
  4833.2    1677  4843.2 1677.11  4863.2 1676.92  4883.2 1677.06  4893.2 1676.97
  4903.2 1676.75  4923.2 1674.63  4943.2 1672.84  4953.2 1673.24  4971.3 1672.75
  4971.5 1672.25    4975 1672.25  4975.3 1672.75  5033.3 1672.84  5043.3 1673.19
  5053.3 1673.97  5073.3 1674.94  5083.3 1674.84  5103.3 1675.12  5113.3 1675.02
  5123.3 1674.62  5133.3 1674.62  5143.3 1674.39  5153.3 1675.51    5179 1676.85
#Mann= 3 ,-1 , 0
  4721.7     .05       0  4971.3     .03       0  4975.3     .05       0
Bank Sta=4971.3,4975.3
XS Rating Curve= 0 ,0
Exp/Cntr=0.3,0.1

Type RM Length L Ch R = 1 ,2590    ,56,56,56
BEGIN DESCRIPTION:
Elm 02 32 2589.87
END DESCRIPTION:
XS GIS Cut Line= 3
      1600462.01       6865166.3      1600434.88      6865339.94
      1600483.47      6865644.44
#Sta/Elev= 30
  4826.3 1676.58  4919.1 1675.73  4929.2  1675.4  4939.4 1673.91  4949.5 1672.72
  4959.6  1672.7    5071  1672.8  5091.2  1673.3  5097.1 1674.44  5102.2  1674.1
  5111.5 1676.42  5121.6 1675.14  5131.7 1673.02  5141.9 1672.62    5150 1671.93
  5150.2 1671.43  5153.7 1671.43    5154 1671.93  5164.3 1672.79  5172.2 1673.13
  5192.5 1673.34  5202.6 1674.01  5212.7 1673.98  5226.4 1674.43    5233 1674.34
  5253.2 1674.79  5273.5 1674.88  5288.5 1675.56  5303.9 1675.49  5310.4 1675.82
#Mann= 3 ,-1 , 0
  4826.3     .05       0    5150     .05       0    5154     .05       0
Bank Sta=5150,5154
XS Rating Curve= 0 ,0
Exp/Cntr=0.3,0.1

Type RM Length L Ch R = 1 ,2534    ,47,47,47
BEGIN DESCRIPTION:
Elm 02 32 2534.37
END DESCRIPTION:
XS GIS Cut Line= 5
      1600427.28      6865145.73      1600384.97      6865320.41
      1600371.94      6865373.58      1600387.14       6865437.6
      1600423.86      6865643.89
#Sta/Elev= 30
  4823.7 1676.25  4900.1 1675.32  4918.6 1675.66  4978.6 1674.96  4983.8 1673.97
  4999.6 1675.46  5020.3 1676.04  5025.5 1675.64  5031.8 1676.69    5063 1676.76
  5090.7 1677.75  5095.9 1676.94  5103.8 1677.64  5114.1 1677.44  5121.6 1675.45
  5126.7 1675.45  5134.5 1673.53    5140 1671.39    5145 1672.67  5152.8 1670.33
  5153.1 1669.83  5156.6 1669.83  5156.8 1670.33    5165 1671.83  5193.9 1673.14
  5215.8 1673.78  5266.6 1674.25  5276.7 1674.75    5297 1674.62  5333.5 1675.78
#Mann= 3 ,-1 , 0
  4823.7     .05       0  5152.8     .05       0  5156.8     .05       0
Bank Sta=5152.8,5156.8
XS Rating Curve= 0 ,0
Exp/Cntr=0.3,0.1

Type RM Length L Ch R = 1 ,2487    ,244,244,244
BEGIN DESCRIPTION:
Elm 02 32 2487.22
END DESCRIPTION:
XS GIS Cut Line= 4
      1600396.91      6865131.58      1600346.99       6865292.2
      1600307.93      6865390.94      1600351.33      6865651.37
#Sta/Elev= 30
    4834 1676.25  4872.1 1676.15    4914 1675.33  4927.2 1674.64  4945.4 1674.65
  4959.7 1673.89  4966.4 1671.33  4976.9 1669.84  5006.4 1669.11  5006.7 1668.61
  5010.2 1668.61  5010.4 1669.11  5101.3 1669.95  5105.6 1670.33  5115.5 1670.36
  5120.8 1670.87  5125.9 1670.31  5135.8  1671.2    5146 1671.17  5176.4 1672.15
  5181.6 1672.58  5186.7 1672.32  5206.8 1672.55  5216.9 1673.02  5287.9 1674.07
  5303.3 1674.72  5328.4 1674.53  5338.6 1675.28  5348.7 1675.13  5372.4 1675.51
#Mann= 3 ,-1 , 0
    4834     .05       0  5006.4     .05       0  5010.4     .05       0
Bank Sta=5006.4,5010.4
XS Rating Curve= 0 ,0
Exp/Cntr=0.3,0.1

Type RM Length L Ch R = 1 ,2243    ,255,255,255
BEGIN DESCRIPTION:
Elm 02 32 2243.13
END DESCRIPTION:
XS GIS Cut Line= 3
      1600258.85      6865042.63      1600104.75      6865282.47
      1600009.64      6865452.15
#Sta/Elev= 30
  4714.4 1673.96  4728.8 1674.05  4749.9 1673.42  4780.2 1673.21  4792.2 1672.68
  4828.5 1672.34  4858.9 1671.73  4864.8 1671.34  4937.5 1669.89  4946.6 1668.15
  4952.7 1666.59  4967.9 1667.41  4982.3 1666.32    4987 1665.44  4987.2 1664.94
  4990.7 1664.94    4991 1665.44  4999.5 1665.58  5026.3 1666.93  5032.1 1666.98
    5048 1668.44  5063.1 1668.81  5069.7 1669.23  5075.4 1668.79  5091.4 1669.18
  5113.1 1670.17    5129 1671.31  5156.5 1671.69  5172.4 1672.38    5194 1672.42
#Mann= 3 ,-1 , 0
  4714.4     .05       0    4987     .05       0    4991     .05       0
Bank Sta=4987,4991
XS Rating Curve= 0 ,0
Exp/Cntr=0.3,0.1

Type RM Length L Ch R = 1 ,1988    ,377,377,377
BEGIN DESCRIPTION:
Elm 02 32 1988.08
END DESCRIPTION:
XS GIS Cut Line= 3
      1600169.88      6864903.75      1599956.09      6865084.98
      1599824.84      6865212.98
#Sta/Elev= 30
  4722.6 1672.73  4807.7 1670.95  4828.5 1669.62  4871.4 1668.57  4885.7 1667.24
  4892.2  1667.1  4906.5 1664.84    4913  1664.7  4920.8 1663.06  4935.1 1662.47
  4941.6 1662.68  4970.2 1661.74  4975.9 1661.25  4976.2 1660.75  4979.7 1660.75
  4979.9 1661.25  4984.5 1661.26  4998.8 1662.71  5007.1 1662.84  5012.9 1664.67
  5019.8 1665.33    5027 1667.28    5034 1667.83  5041.2  1668.9  5069.4 1669.29
  5090.6 1669.07  5097.7 1669.75    5126 1670.35  5154.3 1670.16  5186.2 1670.88
#Mann= 3 ,-1 , 0
  4722.6     .05       0  4975.9     .05       0  4979.9     .05       0
Bank Sta=4975.9,4979.9
XS Rating Curve= 0 ,0
Exp/Cntr=0.3,0.1