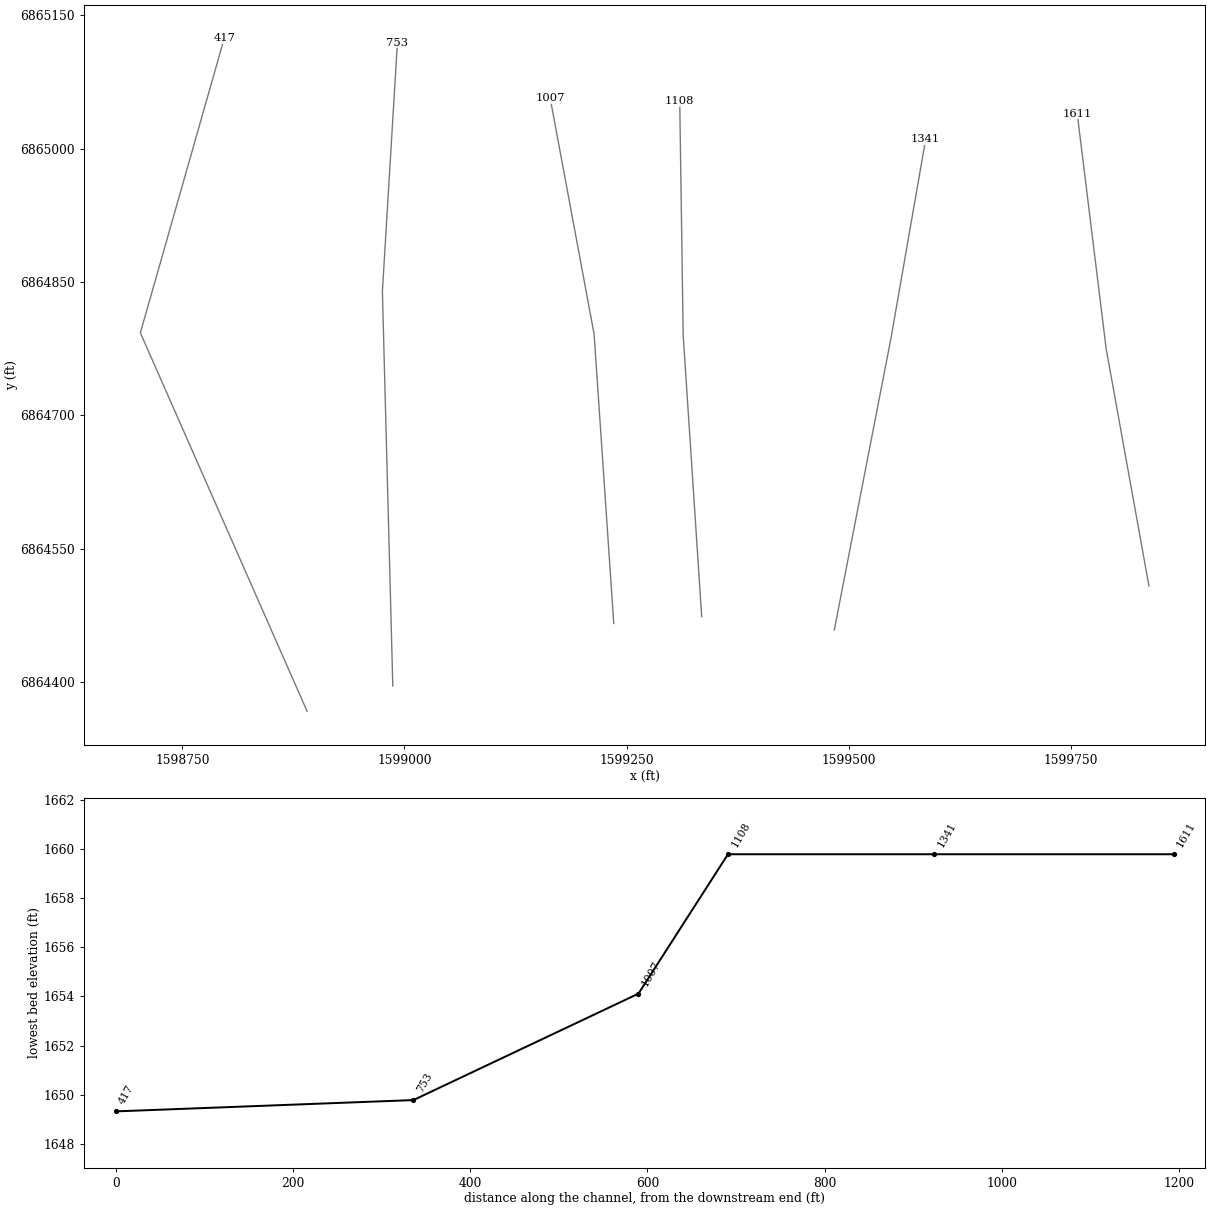
HEC-RAS study Elm 02 32.prj: Elm 02 32 Base Level Engineering

--- Elm 02 32.g01 (geometry) --- (continued)

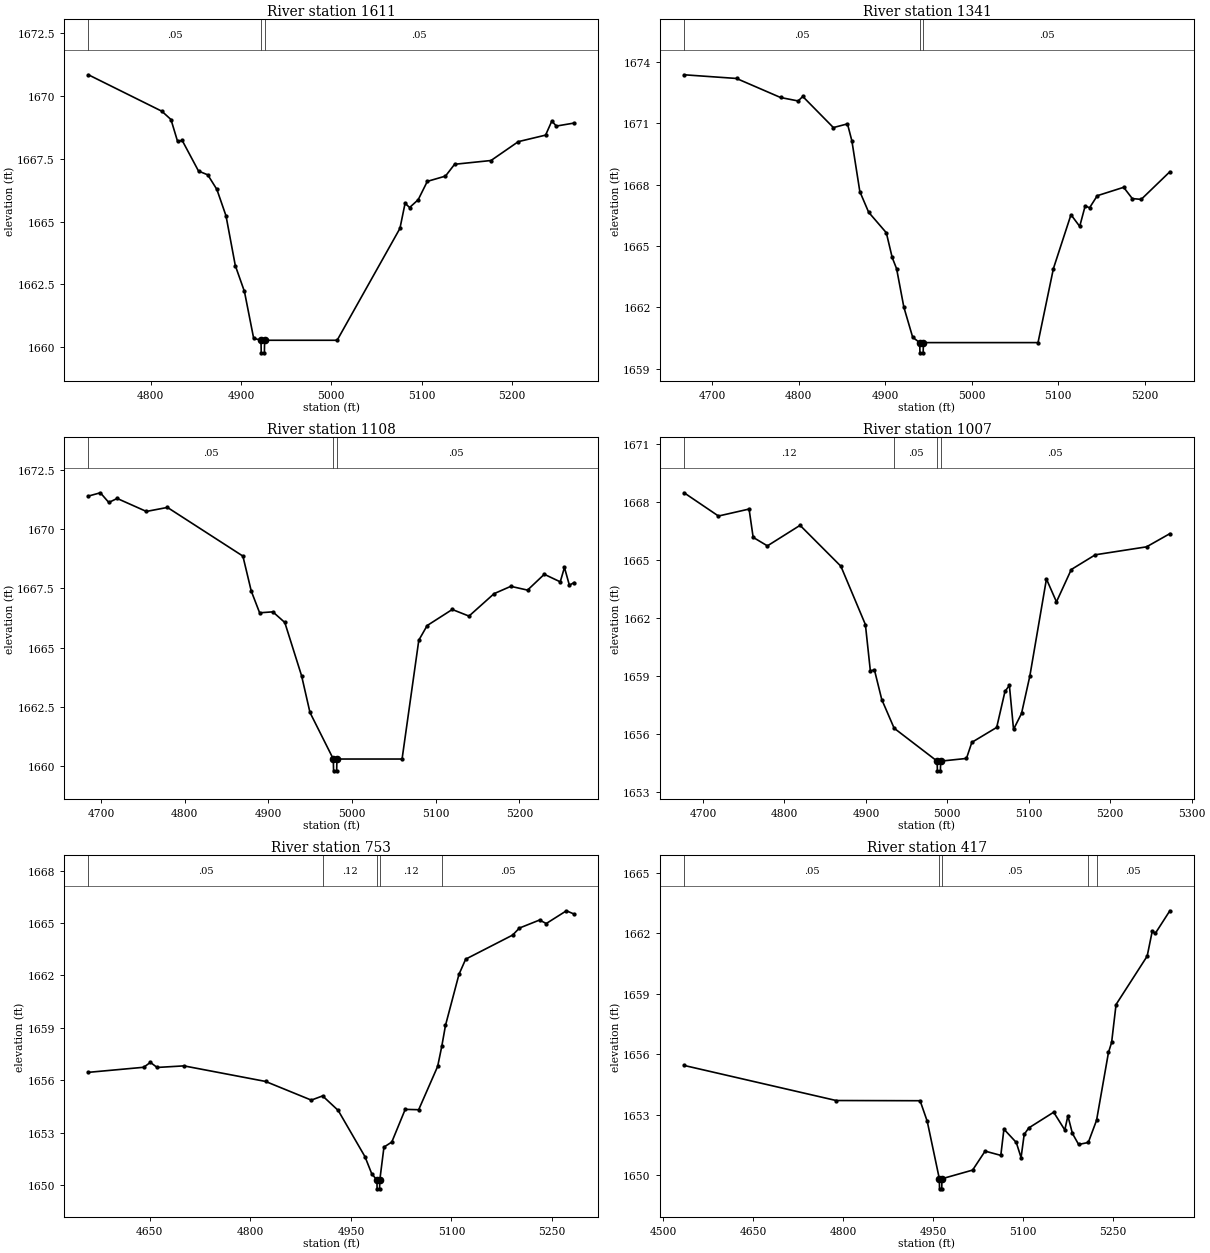
Type RM Length L Ch R = 1 ,1611    ,270,270,270
BEGIN DESCRIPTION:
Elm 02 32 1611.48
END DESCRIPTION:
XS GIS Cut Line= 3
      1599837.93      6864508.03      1599789.75      6864774.98
       1599757.2      6865039.32
#Sta/Elev= 30
  4731.1 1670.84  4812.4 1669.39  4822.5 1669.06  4829.8 1668.19  4834.9 1668.23
    4853 1667.01  4863.2 1666.86  4873.3 1666.28  4883.4 1665.23  4893.7 1663.25
  4903.8 1662.22    4914 1660.36  4922.1 1660.28  4922.4 1659.78  4925.9 1659.78
  4926.1 1660.28  5006.4 1660.28  5075.9 1664.73  5081.6 1665.73  5086.6 1665.56
  5096.1 1665.87  5106.2  1666.6  5126.3 1666.81  5136.4 1667.28  5176.7 1667.43
  5206.9 1668.18  5237.1 1668.44    5244    1669    5249  1668.8  5268.7 1668.92
#Mann= 3 ,-1 , 0
  4731.1     .05       0  4922.1     .05       0  4926.1     .05       0
Bank Sta=4922.1,4926.1
XS Rating Curve= 0 ,0
Exp/Cntr=0.3,0.1

Type RM Length L Ch R = 1 ,1341    ,233,233,233
BEGIN DESCRIPTION:
Elm 02 32 1341.31
END DESCRIPTION:
XS GIS Cut Line= 3
      1599483.75      6864458.54      1599547.56       6864786.7
      1599586.62      6865010.61
#Sta/Elev= 30
  4667.6 1673.37  4728.2 1673.19  4779.1 1672.26  4799.5 1672.09  4804.8 1672.31
  4840.2 1670.79  4856.5 1670.97  4861.6 1670.14  4870.8 1667.66    4881 1666.65
  4901.4 1665.65  4908.2 1664.44  4913.3 1663.89  4921.7 1662.01  4931.9 1660.54
    4940 1660.28  4940.3 1659.78    4944 1659.78  4944.3 1660.28  5076.8 1660.28
  5094.6  1663.9  5114.9 1666.53    5125 1665.96  5131.3 1666.96  5136.4 1666.87
  5145.3 1667.46  5175.8 1667.87  5185.8 1667.32  5196.1 1667.28  5229.2 1668.63
#Mann= 3 ,-1 , 0
  4667.6     .05       0    4940     .05       0  4944.3     .05       0
Bank Sta=4940,4944.3
XS Rating Curve= 0 ,0
Exp/Cntr=0.3,0.1

Type RM Length L Ch R = 1 ,1108    ,101,101,101
BEGIN DESCRIPTION:
Elm 02 32 1107.56
END DESCRIPTION:
XS GIS Cut Line= 3
      1599334.54       6864473.7      1599313.71      6864790.08
      1599309.81      6865053.68
#Sta/Elev= 30
  4684.8 1671.41  4699.1 1671.55  4709.2 1671.14  4719.2 1671.31  4754.1 1670.76
  4779.3 1670.93  4869.5 1668.87  4879.5 1667.39  4889.5 1666.47  4905.3 1666.51
  4919.6 1666.06  4939.7  1663.8  4949.7 1662.25  4977.6 1660.28  4977.9 1659.78
  4981.6 1659.78  4981.9 1660.28  5059.8 1660.28  5079.8 1665.31  5089.8 1665.93
  5119.8 1666.61  5139.8 1666.33  5169.8 1667.28  5189.8 1667.59  5209.8 1667.43
  5229.8  1668.1  5248.9 1667.78  5253.9 1668.39  5259.8 1667.64  5265.5 1667.75
#Mann= 3 ,-1 , 0
  4684.8     .05       0  4977.6     .05       0  4981.9     .05       0
Bank Sta=4977.6,4981.9
XS Rating Curve= 0 ,0
Exp/Cntr=0.3,0.1

Type RM Length L Ch R = 1 ,1007    ,254,254,254
BEGIN DESCRIPTION:
Elm 02 32 1007.38
END DESCRIPTION:
XS GIS Cut Line= 3
      1599235.58      6864465.89      1599213.45      6864791.39
      1599163.98      6865056.97
#Sta/Elev= 30
  4676.8 1668.46    4719 1667.26  4756.6 1667.62  4761.6 1666.16  4779.1 1665.72
  4819.2 1666.78  4869.3 1664.67  4899.4 1661.66  4905.5 1659.27  4910.5 1659.32
  4919.5 1657.79  4934.7 1656.31  4987.5 1654.61  4987.8 1654.11  4991.5 1654.11
  4991.8 1654.61  5023.5 1654.75  5030.1 1655.58  5060.6 1656.35  5070.8 1658.21
  5076.2 1658.52  5081.3 1656.25  5091.1 1657.07  5101.3    1659  5121.7 1664.01
    5134 1662.83  5152.2  1664.5  5181.7 1665.26  5244.6 1665.67  5273.2 1666.35
#Mann= 4 ,-1 , 0
  4676.8     .12       0  4934.7     .05       0  4987.5     .05       0
  4991.8     .05       0
Bank Sta=4987.5,4991.8
XS Rating Curve= 0 ,0
Exp/Cntr=0.3,0.1

Type RM Length L Ch R = 1 ,753     ,336,336,336
BEGIN DESCRIPTION:
Elm 02 32 753.18
END DESCRIPTION:
XS GIS Cut Line= 3
      1598986.89      6864395.57      1598975.17      6864839.56
      1598992.09      6865119.51
#Sta/Elev= 30
  4558.4 1656.45  4640.9 1656.74  4650.9 1657.02  4660.9 1656.73  4700.9 1656.82
  4822.6 1655.93  4890.9 1654.86  4907.8  1655.1    4931 1654.27    4971 1651.62
    4981 1650.65  4988.8 1650.28  4989.1 1649.78  4992.8 1649.78  4993.1 1650.28
  4999.3 1652.17    5011 1652.46    5031 1654.33  5051.1 1654.31  5079.4 1656.79
  5085.5 1657.93  5091.1 1659.14  5111.2 1662.06  5121.2 1662.93  5191.3 1664.31
  5201.3 1664.71  5231.4 1665.17  5241.4 1664.97  5271.5  1665.7    5283 1665.51
#Mann= 5 ,-1 , 0
  4558.4     .05       0  4907.8     .12       0  4988.8     .07       0
  4993.1     .12       0  5085.5     .05       0
Bank Sta=4988.8,4993.1
XS Rating Curve= 0 ,0
Exp/Cntr=0.3,0.1

Type RM Length L Ch R = 1 ,417     ,0,0,0
BEGIN DESCRIPTION:
Elm 02 32 956.889
END DESCRIPTION:
XS GIS Cut Line= 3
      1598890.52      6864366.94      1598702.77      6864792.89
       1598797.2      6865124.31
#Sta/Elev= 30
  4534.5 1655.44  4788.1  1653.7  4928.1 1653.69    4940 1652.67  4960.2 1649.82
  4960.5 1649.32  4964.2 1649.32  4964.5 1649.82  5015.7 1650.25  5036.5 1651.19
  5062.7 1650.98  5067.9 1652.28  5088.5 1651.62  5096.5 1650.87  5101.7 1652.02
  5109.3 1652.34  5150.9 1653.12  5169.4 1652.24  5174.6 1652.94  5182.1 1652.07
  5192.5 1651.52  5208.6 1651.62  5222.4 1652.72  5242.3 1656.09  5247.5 1656.58
  5254.9 1658.46  5306.8 1660.86  5315.2 1662.09  5320.4 1661.99  5344.6 1663.11
#Mann= 5 ,-1 , 0
  4534.5     .05       0  4960.2     .05       0  4964.5     .05       0
  5208.6     .12       0  5222.4     .05       0
Bank Sta=4960.2,4964.5
XS Rating Curve= 0 ,0
Exp/Cntr=0.3,0.1

Chan Stop Cuts=-1
Use User Specified Reach Order=0
Composite Channel Slope=5