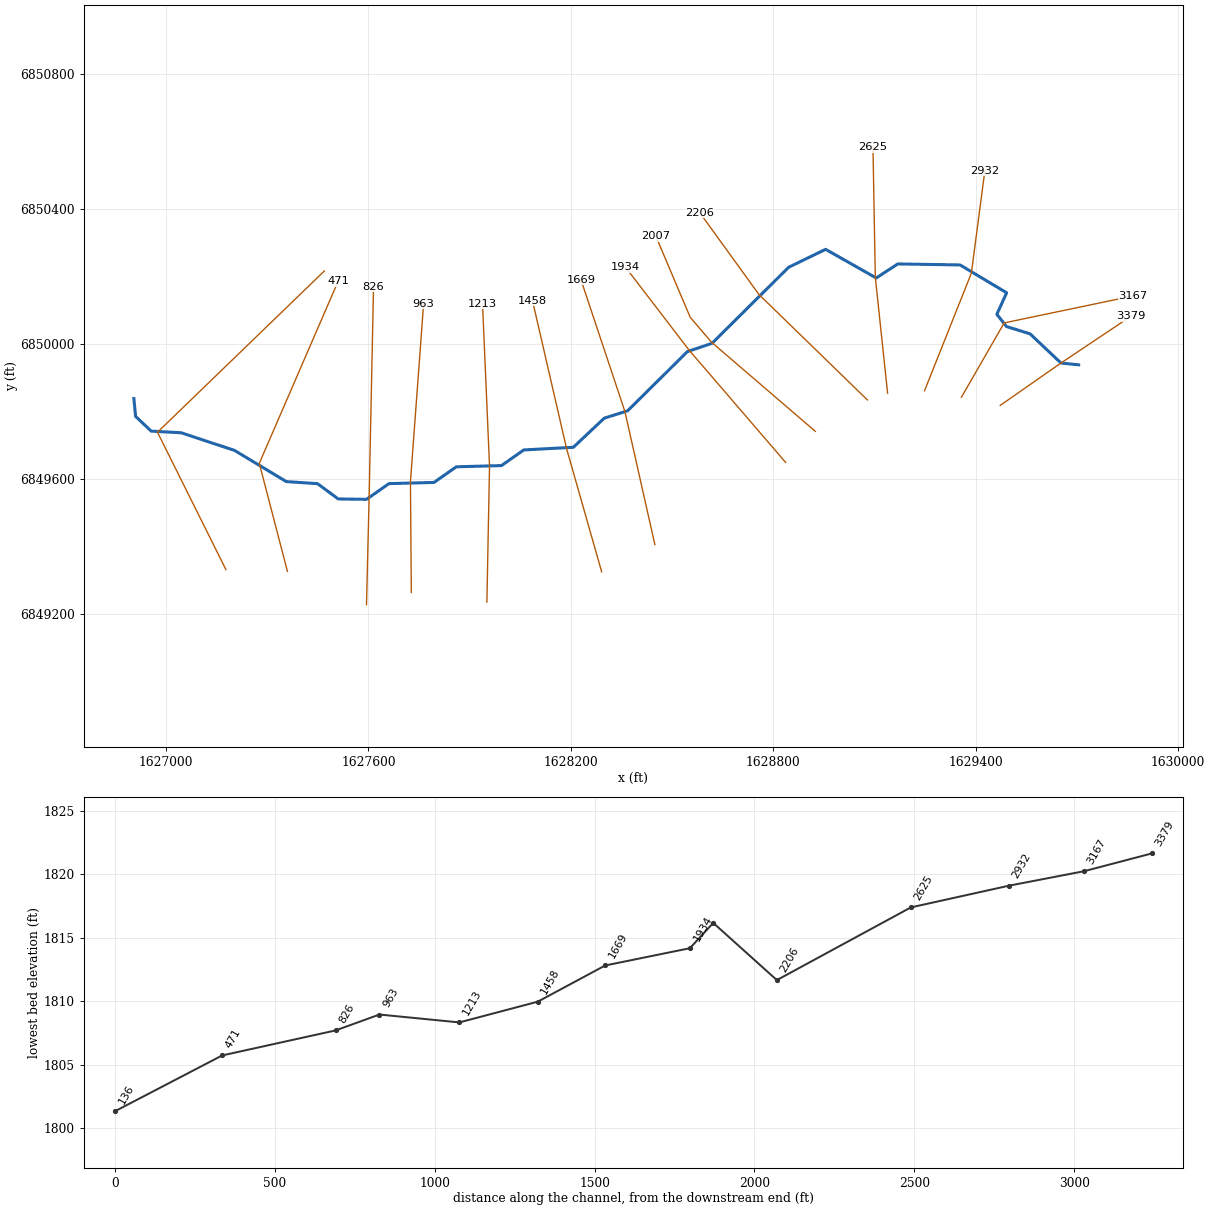
--- Elm 02 33.prj (project) ---

Proj Title=Elm 02 33 Base Level Engineering
Current Plan=p01
Default Exp/Contr=0.3,0.1
English Units
Geom File=g01
Flow File=f01
Plan File=p01
BEGIN DESCRIPTION:
Elm 02 33
END DESCRIPTION:

--- Elm 02 33.p01 (plan) ---

Plan Title=Multiple Run
Short Identifier=Multiple
Geom File=g01
Flow File=f01
Subcritical Flow
K Sum by GR= 0
Std Step Tol= 0.01
Critical Tol= 0.01
Num of Std Step Trials= 20
Max Error Tol= 0.3
Flow Tol Ratio= 0.001
Split Flow NTrial= 30
Split Flow Tol= 0.02
Split Flow Ratio= 0.02
Log Output Level= 0
Friction Slope Method= 1
Unsteady Friction Slope Method= 2
Unsteady Bridges Friction Slope Method= 1
Parabolic Critical Depth
Global Vel Dist=  1 , 1 , 1
Global Log Level= 0
CheckData=True
Encroach Param= -1, 0, 0, 0
BEGIN DESCRIPTION:
Multiple Run
END DESCRIPTION:

--- Elm 02 33.f01 (steady flow) ---

Flow Title=Multiple
Number of Profiles=7
Profile Names=10-year,25-year,50-year,1pct_min,100-year,1pct_plu,500-year
River Rch & RM= Elm 02 33,Reach-1,3379
     176     239     290     219     350     482     518
River Rch & RM= Elm 02 33,Reach-1,2932
     282     394     488     375     601     826     921
Boundary for River Rch & Prof#=Elm 02 33,Reach-1,1
Up Type=0
Dn Type=3
Dn Slope=0.001
Boundary for River Rch & Prof#=Elm 02 33,Reach-1,2
Up Type=0
Dn Type=3
Dn Slope=0.001
Boundary for River Rch & Prof#=Elm 02 33,Reach-1,3
Up Type=0
Dn Type=3
Dn Slope=0.001
Boundary for River Rch & Prof#=Elm 02 33,Reach-1,4
Up Type=0
Dn Type=3
Dn Slope=0.001
Boundary for River Rch & Prof#=Elm 02 33,Reach-1,5
Up Type=0
Dn Type=3
Dn Slope=0.001
Boundary for River Rch & Prof#=Elm 02 33,Reach-1,6
Up Type=0
Dn Type=3
Dn Slope=0.001
Boundary for River Rch & Prof#=Elm 02 33,Reach-1,7
Up Type=0
Dn Type=3
Dn Slope=0.001

--- Elm 02 33.g01 (geometry) ---

Geom Title=Existing Conditions

River Reach=Elm 02 33,Reach-1
Reach XY= 30
      1629705.00      6849938.00      1629652.49      6849943.33
      1629561.01      6850029.84      1629491.00      6850051.63
      1629462.48      6850087.80      1629491.49      6850151.68
      1629353.45      6850234.25      1629168.86      6850237.17
      1629104.99      6850195.53      1628955.00      6850280.50
      1628845.32      6850227.25      1628618.21      6850001.63
      1628545.32      6849977.22      1628368.21      6849801.63
      1628298.96      6849779.82      1628207.44      6849693.48
      1628060.53      6849685.61      1627994.49      6849639.23
      1627860.53      6849635.61      1627794.49      6849589.23
      1627660.94      6849585.73      1627594.45      6849539.10
      1627510.57      6849540.28      1627449.43      6849585.53
      1627356.58      6849591.83      1627203.42      6849684.17
      1627045.29      6849736.51      1626956.30      6849741.46
      1626910.13      6849785.06      1626905.00      6849838.00

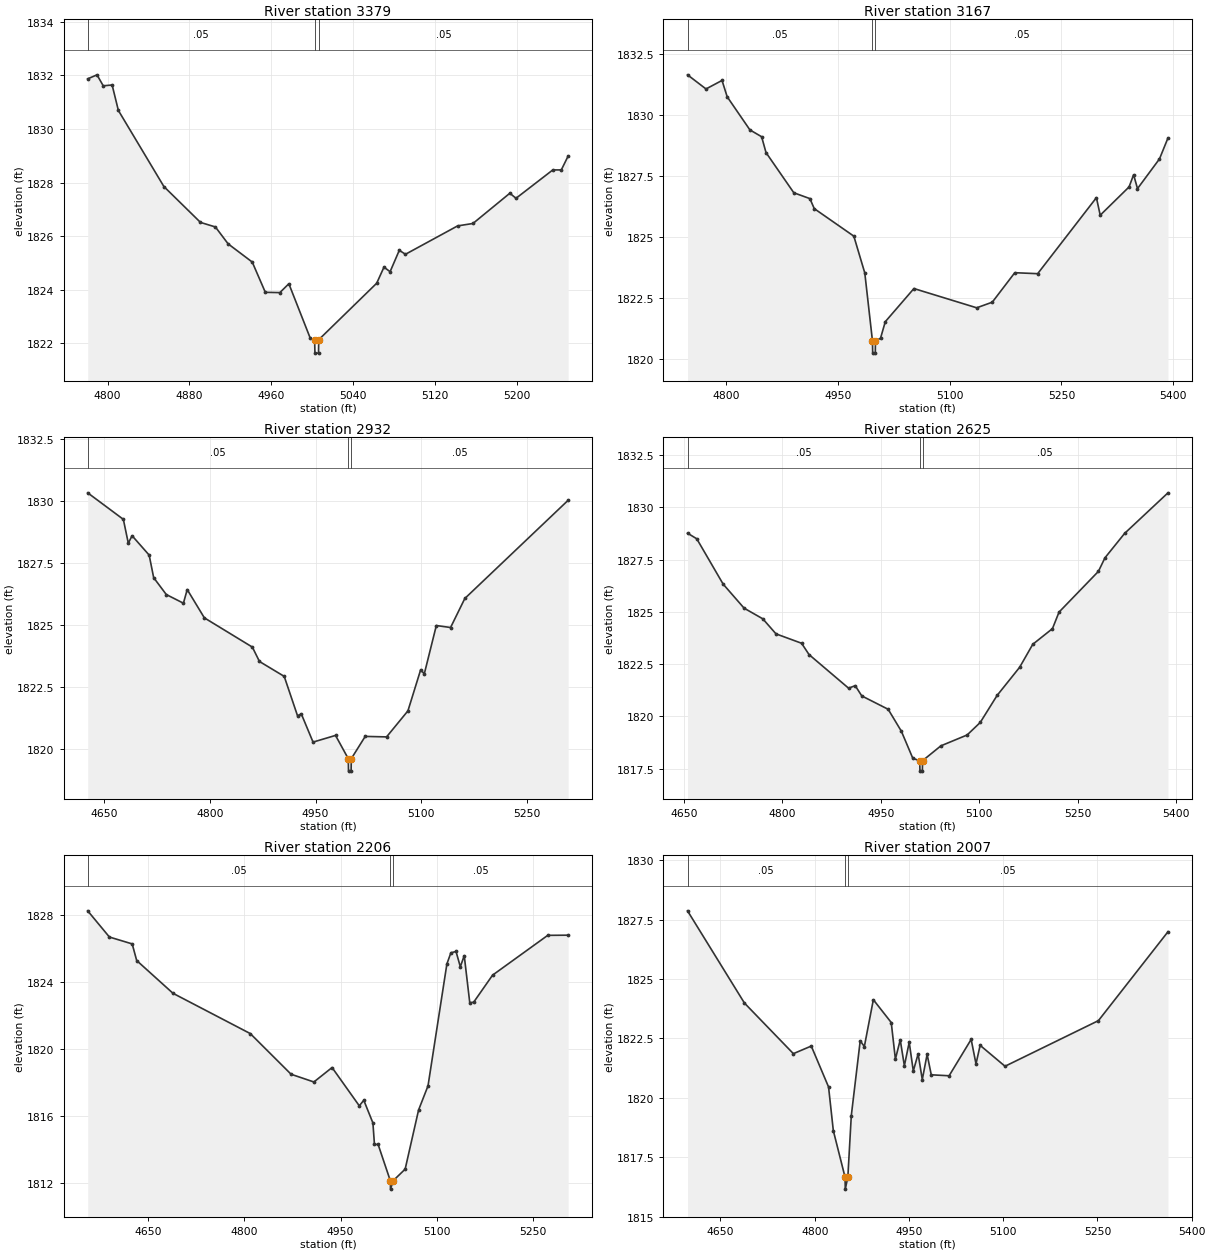
Type RM Length L Ch R = 1,3379,212,212,212
BEGIN DESCRIPTION:
Elm 02 33 3378.947
END DESCRIPTION:
XS GIS Cut Line= 3
      1629472.59      6849817.75      1629652.49      6849943.33
      1629860.61      6850082.57
#Sta/Elev= 30
  4780.6 1831.87  4789.7 1832.02  4795.8 1831.61  4804.5 1831.64  4810.6 1830.69
  4855.1 1827.85  4890.9 1826.51  4905.5 1826.34  4917.9 1825.71  4941.5 1825.03
  4954.3 1823.90  4968.5 1823.89  4977.3 1824.22  4998.2 1822.19  5002.5 1822.13
  5002.8 1821.63  5006.3 1821.63  5006.5 1822.13  5063.2 1824.24  5070.3 1824.84
  5076.3 1824.67  5085.3 1825.47  5091.3 1825.32  5142.3 1826.38  5157.3 1826.47
  5193.4 1827.60  5199.4 1827.41  5235.4 1828.47  5243.7 1828.47  5250.4 1828.99
#Mann=3,-1,0
  4780.6    0.05       0  5002.5    0.05       0  5006.5    0.05       0
Bank Sta=5002.5,5006.5
Exp/Cntr=0.3,0.1

Type RM Length L Ch R = 1,3167,235,235,235
BEGIN DESCRIPTION:
Elm 02 33 3166.97
END DESCRIPTION:
XS GIS Cut Line= 3
      1629357.47      6849841.86      1629484.21      6850062.35
      1629866.13      6850142.21
#Sta/Elev= 30
  4748.5 1831.65  4773.3 1831.07  4794.8 1831.42  4801.7 1830.75  4832.2 1829.39
  4847.9 1829.11  4853.8 1828.46  4891.1 1826.81  4912.7 1826.57  4918.5 1826.16
  4971.6 1825.03  4986.3 1823.52  4996.6 1820.73  4996.9 1820.23  5000.4 1820.23
  5000.6 1820.73  5007.4 1820.84  5013.8 1821.52  5052.2 1822.88  5136.4 1822.09
  5157.3 1822.32  5187.5 1823.53  5218.2 1823.49  5297.0 1826.61  5302.1 1825.89
  5340.8 1827.05  5346.9 1827.55  5352.1 1826.98  5381.6 1828.20  5393.0 1829.06
#Mann=3,-1,0
  4748.5    0.05       0  4996.6    0.05       0  5000.6    0.05       0
Bank Sta=4996.6,5000.6
Exp/Cntr=0.3,0.1

Type RM Length L Ch R = 1,2932,307,307,307
BEGIN DESCRIPTION:
Elm 02 33 2931.71
END DESCRIPTION:
XS GIS Cut Line= 3
      1629248.11      6849861.00      1629386.99      6850209.92
      1629426.87      6850513.37
#Sta/Elev= 30
  4626.8 1830.31  4677.4 1829.24  4684.4 1828.28  4689.8 1828.58  4714.0 1827.80
  4720.4 1826.89  4738.3 1826.21  4762.6 1825.86  4768.0 1826.41  4792.3 1825.27
  4860.4 1824.09  4870.5 1823.51  4905.6 1822.91  4924.5 1821.32  4929.8 1821.40
  4946.5 1820.26  4978.4 1820.53  4996.5 1819.59  4996.8 1819.09  5000.5 1819.09
  5000.7 1819.59  5020.5 1820.49  5050.8 1820.47  5081.1 1821.52  5099.2 1823.18
  5104.3 1823.01  5121.4 1824.96  5141.6 1824.88  5161.8 1826.05  5308.4 1830.01
#Mann=3,-1,0
  4626.8    0.05       0  4996.5    0.03       0  5000.7    0.05       0
Bank Sta=4996.5,5000.7
Exp/Cntr=0.3,0.1

Type RM Length L Ch R = 1,2625,419,419,419
BEGIN DESCRIPTION:
Elm 02 33 2624.6
END DESCRIPTION:
XS GIS Cut Line= 3
      1629138.73      6849853.97      1629102.27      6850197.77
      1629095.34      6850583.98
#Sta/Elev= 30
  4655.5 1828.77  4669.6 1828.50  4709.8 1826.33  4741.7 1825.18  4770.2 1824.67
  4790.3 1823.95  4829.3 1823.50  4840.6 1822.96  4900.9 1821.35  4911.0 1821.47
  4921.0 1820.98  4961.2 1820.34  4981.3 1819.29  4998.8 1817.99  5009.3 1817.88
  5009.6 1817.38  5013.3 1817.38  5013.6 1817.88  5041.5 1818.59  5081.5 1819.11
  5101.5 1819.71  5127.1 1821.00  5161.5 1822.35  5181.5 1823.45  5211.5 1824.20
  5221.5 1824.99  5281.5 1826.94  5291.5 1827.59  5321.5 1828.76  5387.5 1830.70
#Mann=3,-1,0
  4655.5    0.05       0  5009.3    0.05       0  5013.6    0.05       0
Bank Sta=5009.3,5013.6
Exp/Cntr=0.3,0.1

Type RM Length L Ch R = 1,2206,199,199,199
BEGIN DESCRIPTION:
Elm 02 33 2206.45
END DESCRIPTION:
XS GIS Cut Line= 3
      1629078.82      6849833.88      1628757.65      6850146.37
      1628581.85      6850389.45
#Sta/Elev= 30
  4556.3 1828.23  4590.1 1826.67  4625.6 1826.26  4632.6 1825.27  4689.1 1823.32
  4809.5 1820.92  4873.0 1818.50  4908.5 1818.04  4936.8 1818.90  4979.2 1816.62
  4986.2 1816.95  5000.4 1815.60  5002.8 1814.32  5008.5 1814.32  5027.5 1812.16
  5027.8 1811.66  5031.9 1812.16  5050.6 1812.85  5071.5 1816.37  5086.2 1817.81
  5115.6 1825.07  5121.8 1825.73  5129.8 1825.81  5136.5 1824.90  5142.6 1825.56
  5151.2 1822.76  5157.3 1822.79  5186.7 1824.40  5272.6 1826.77  5304.4 1826.78
#Mann=3,-1,0
  4556.3    0.05       0  5027.5    0.05       0  5031.9    0.05       0
Bank Sta=5027.5,5031.9
Exp/Cntr=0.3,0.1

Type RM Length L Ch R = 1,2007,73,73,73
BEGIN DESCRIPTION:
Elm 02 33 2007.18
END DESCRIPTION:
XS GIS Cut Line= 4
      1628924.74      6849740.56      1628616.59      6850005.31
      1628553.66      6850079.10      1628451.67      6850319.95
#Sta/Elev= 30
  4597.5 1827.87  4688.1 1823.99  4766.0 1821.86  4794.5 1822.18  4822.0 1820.46
  4829.6 1818.62  4848.3 1816.66  4848.6 1816.16  4852.7 1816.66  4858.2 1819.25
  4872.4 1822.40  4879.0 1822.16  4893.3 1824.13  4921.8 1823.17  4928.4 1821.63
  4936.1 1822.44  4942.7 1821.35  4950.4 1822.34  4956.9 1821.13  4964.6 1821.85
  4971.2 1820.77  4978.9 1821.83  4985.5 1820.97  5013.9 1820.93  5049.0 1822.46
  5056.7 1821.43  5063.3 1822.21  5102.9 1821.33  5251.6 1823.25  5362.3 1826.99
#Mann=3,-1,0
  4597.5    0.05       0  4848.3    0.05       0  4852.7    0.05       0
Bank Sta=4848.3,4852.7
Exp/Cntr=0.3,0.1

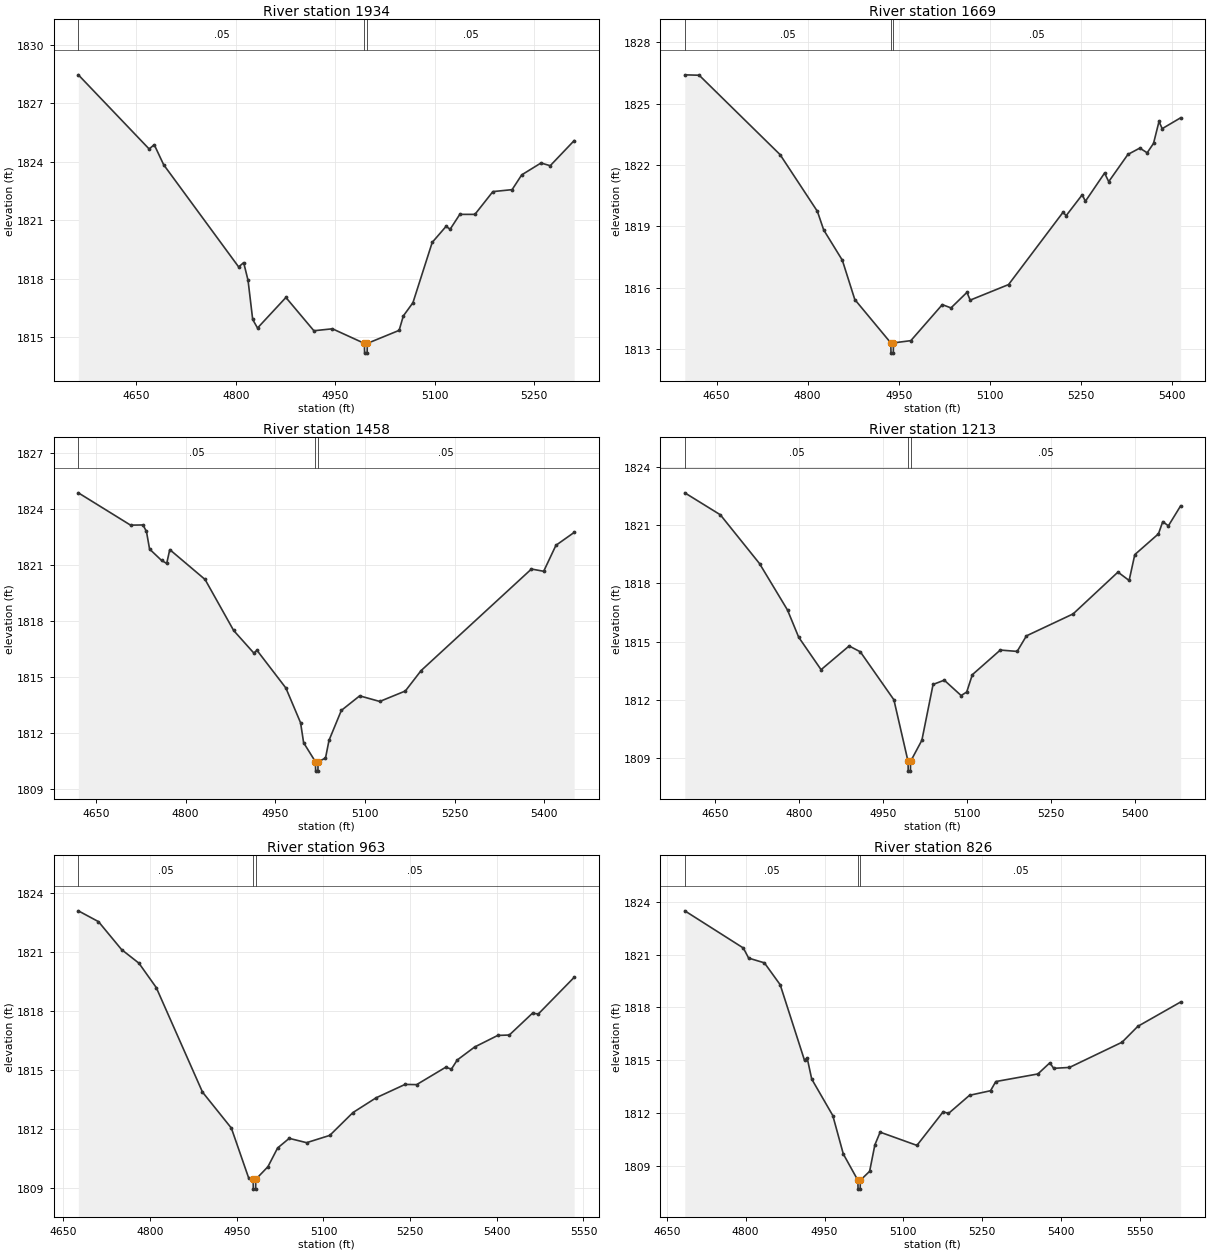
Type RM Length L Ch R = 1,1934,265,265,265
BEGIN DESCRIPTION:
Elm 02 33 1934.03
END DESCRIPTION:
XS GIS Cut Line= 3
      1628836.62      6849648.53      1628550.15      6849981.88
      1628362.64      6850226.68
#Sta/Elev= 30
  4562.4 1828.47  4669.2 1824.66  4676.9 1824.88  4691.1 1823.85  4804.2 1818.60
  4811.8 1818.82  4818.4 1817.91  4825.4 1815.90  4832.7 1815.46  4875.5 1817.03
  4917.7 1815.32  4945.7 1815.42  4993.9 1814.67  4994.2 1814.17  4998.0 1814.17
  4998.3 1814.67  5046.3 1815.34  5052.6 1816.08  5067.1 1816.76  5096.2 1819.86
  5117.0 1820.68  5123.3 1820.54  5137.8 1821.30  5160.6 1821.30  5187.7 1822.47
  5216.7 1822.57  5231.2 1823.33  5260.3 1823.94  5274.2 1823.80  5310.3 1825.09
#Mann=3,-1,0
  4562.4    0.05       0  4993.9    0.05       0  4998.3    0.05       0
Bank Sta=4993.9,4998.3
Exp/Cntr=0.3,0.1

Type RM Length L Ch R = 1,1669,211,211,211
BEGIN DESCRIPTION:
Elm 02 33 1669.06
END DESCRIPTION:
XS GIS Cut Line= 3
      1628449.06      6849404.92      1628360.08      6849799.91
      1628229.95      6850190.30
#Sta/Elev= 30
  4597.8 1826.41  4621.5 1826.39  4754.7 1822.51  4816.1 1819.74  4826.5 1818.83
  4857.2 1817.35  4877.7 1815.43  4937.0 1813.31  4937.3 1812.81  4941.1 1812.81
  4941.4 1813.31  4970.0 1813.42  5021.8 1815.18  5036.1 1815.02  5062.4 1815.78
  5067.7 1815.40  5130.9 1816.16  5220.5 1819.69  5225.8 1819.53  5252.2 1820.55
  5257.4 1820.23  5289.0 1821.61  5295.8 1821.19  5327.4 1822.52  5347.0 1822.83
  5359.1 1822.60  5369.6 1823.06  5378.6 1824.13  5383.9 1823.78  5414.2 1824.31
#Mann=3,-1,0
  4597.8    0.05       0  4937.0    0.05       0  4941.4    0.05       0
Bank Sta=4937,4941.4
Exp/Cntr=0.3,0.1

Type RM Length L Ch R = 1,1458,245,245,245
BEGIN DESCRIPTION:
Elm 02 33 1457.82
END DESCRIPTION:
XS GIS Cut Line= 3
      1628291.35      6849323.97      1628187.19      6849690.25
      1628086.50      6850127.71
#Sta/Elev= 30
  4620.5 1824.86  4707.9 1823.13  4728.7 1823.14  4734.5 1822.79  4739.7 1821.85
  4759.8 1821.24  4768.4 1821.08  4773.5 1821.82  4832.6 1820.22  4880.4 1817.49
  4914.2 1816.28  4919.4 1816.43  4967.8 1814.41  4992.4 1812.55  4997.5 1811.48
  5017.3 1810.46  5017.6 1809.96  5021.4 1809.96  5021.7 1810.46  5034.1 1810.66
  5040.0 1811.61  5060.6 1813.21  5091.3 1813.99  5124.9 1813.69  5167.7 1814.25
  5194.0 1815.34  5378.7 1820.78  5399.2 1820.66  5419.7 1822.05  5450.2 1822.74
#Mann=3,-1,0
  4620.5    0.05       0  5017.3    0.05       0  5021.7    0.05       0
Bank Sta=5017.3,5021.7
Exp/Cntr=0.3,0.1

Type RM Length L Ch R = 1,1213,250,250,250
BEGIN DESCRIPTION:
Elm 02 33 1213.44
END DESCRIPTION:
XS GIS Cut Line= 3
      1627951.19      6849234.50      1627959.00      6849638.13
      1627938.17      6850119.87
#Sta/Elev= 30
  4595.5 1822.65  4659.0 1821.52  4729.0 1819.01  4779.0 1816.62  4799.0 1815.22
  4839.0 1813.55  4889.1 1814.77  4909.1 1814.47  4969.1 1812.00  4994.4 1808.83
  4994.7 1808.33  4998.6 1808.33  4998.9 1808.83  5019.1 1809.92  5039.1 1812.79
  5059.1 1813.01  5089.2 1812.22  5099.2 1812.40  5109.2 1813.29  5159.2 1814.56
  5189.3 1814.49  5205.9 1815.29  5289.3 1816.42  5369.4 1818.57  5389.4 1818.14
  5399.5 1819.47  5441.8 1820.54  5449.5 1821.17  5459.5 1820.95  5481.4 1821.98
#Mann=3,-1,0
  4595.5    0.05       0  4994.4    0.05       0  4998.9    0.05       0
Bank Sta=4994.4,4998.9
Exp/Cntr=0.3,0.1

Type RM Length L Ch R = 1,963,137,137,137
BEGIN DESCRIPTION:
Elm 02 33 963.42
END DESCRIPTION:
XS GIS Cut Line= 3
      1627727.23      6849263.11      1627724.63      6849591.25
      1627763.69      6850119.86
#Sta/Elev= 30
  4675.7 1823.09  4710.6 1822.54  4750.6 1821.12  4780.6 1820.43  4810.6 1819.19
  4890.6 1813.88  4940.6 1812.05  4970.6 1809.51  4978.3 1809.45  4978.6 1808.95
  4982.6 1808.95  4982.9 1809.45  5003.9 1810.09  5020.6 1811.04  5040.7 1811.53
  5070.8 1811.31  5110.9 1811.68  5151.0 1812.84  5191.1 1813.59  5241.2 1814.27
  5261.3 1814.26  5311.4 1815.14  5321.5 1815.05  5331.5 1815.51  5361.6 1816.17
  5401.7 1816.76  5421.7 1816.78  5461.8 1817.89  5471.9 1817.85  5533.9 1819.71
#Mann=3,-1,0
  4675.7    0.05       0  4978.3    0.05       0  4982.9    0.05       0
Bank Sta=4978.3,4982.9
Exp/Cntr=0.3,0.1

Type RM Length L Ch R = 1,826,355,355,355
BEGIN DESCRIPTION:
Elm 02 33 825.93
END DESCRIPTION:
XS GIS Cut Line= 3
      1627594.42      6849226.63      1627602.23      6849546.98
      1627615.25      6850169.40
#Sta/Elev= 30
  4684.2 1823.48  4795.6 1821.37  4805.6 1820.80  4835.6 1820.53  4865.6 1819.29
  4911.9 1815.00  4916.9 1815.14  4925.6 1813.94  4965.7 1811.87  4985.7 1809.69
  5013.4 1808.20  5013.7 1807.70  5017.7 1807.70  5018.0 1808.20  5035.7 1808.71
  5045.7 1810.21  5055.7 1810.93  5125.7 1810.18  5175.7 1812.09  5185.7 1811.99
  5225.7 1813.02  5265.7 1813.28  5275.7 1813.80  5355.7 1814.23  5378.4 1814.86
  5385.8 1814.55  5415.8 1814.60  5515.8 1816.03  5545.8 1816.93  5627.2 1818.31
#Mann=3,-1,0
  4684.2    0.05       0  5013.4    0.03       0  5018.0    0.05       0
Bank Sta=5013.4,5018
Exp/Cntr=0.3,0.1

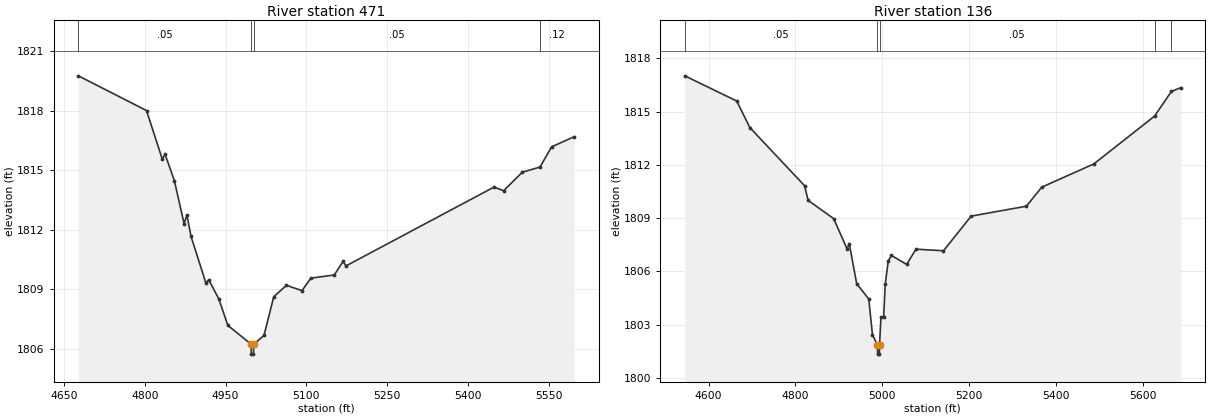
Type RM Length L Ch R = 1,471,335,335,335
BEGIN DESCRIPTION:
Elm 02 33 470.89
END DESCRIPTION:
XS GIS Cut Line= 3
      1627360.05      6849325.60      1627276.71      6849645.94
      1627510.53      6850186.32
#Sta/Elev= 30
  4676.9 1819.76  4803.4 1818.01  4832.6 1815.56  4837.8 1815.81  4855.0 1814.48
  4873.1 1812.31  4878.3 1812.75  4886.0 1811.66  4913.6 1809.31  4918.8 1809.48
  4937.7 1808.50  4954.2 1807.18  4997.5 1806.23  4997.8 1805.73  5001.8 1805.73
  5002.2 1806.23  5021.3 1806.67  5039.4 1808.62  5062.9 1809.20  5091.8 1808.93
  5108.2 1809.56  5151.8 1809.72  5167.7 1810.40  5173.6 1810.18  5447.9 1814.15
  5465.9 1813.97  5500.5 1814.90  5533.3 1815.16  5554.9 1816.18  5596.7 1816.69
#Mann=4,-1,0
  4676.9    0.05       0  4997.5    0.03       0  5002.2    0.05       0
  5533.3    0.12       0
Bank Sta=4997.5,5002.2
Exp/Cntr=0.3,0.1

Type RM Length L Ch R = 1,136,0,0,0
BEGIN DESCRIPTION:
Elm 02 33 500.087
END DESCRIPTION:
XS GIS Cut Line= 3
      1627177.73      6849330.87      1626974.97      6849738.09
      1627469.39      6850216.23
#Sta/Elev= 30
  4545.1 1817.01  4664.8 1815.59  4694.9 1814.10  4821.2 1810.82  4829.2 1810.00
  4888.2 1808.97  4918.8 1807.28  4924.4 1807.53  4941.2 1805.31  4969.1 1804.44
  4977.6 1802.43  4989.2 1801.84  4989.5 1801.34  4993.5 1801.34  4993.9 1801.84
  4997.2 1803.42  5003.5 1803.42  5007.0 1805.27  5014.0 1806.58  5021.2 1806.90
  5056.4 1806.39  5077.8 1807.25  5141.3 1807.16  5205.1 1809.11  5332.4 1809.67
  5367.7 1810.74  5487.8 1812.05  5627.7 1814.74  5666.6 1816.13  5687.8 1816.34
#Mann=5,-1,0
  4545.1    0.05       0  4989.2    0.03       0  4993.9    0.05       0
  5627.7    0.12       0  5666.6    0.05       0
Bank Sta=4989.2,4993.9
Exp/Cntr=0.3,0.1

Chan Stop Cuts=-1