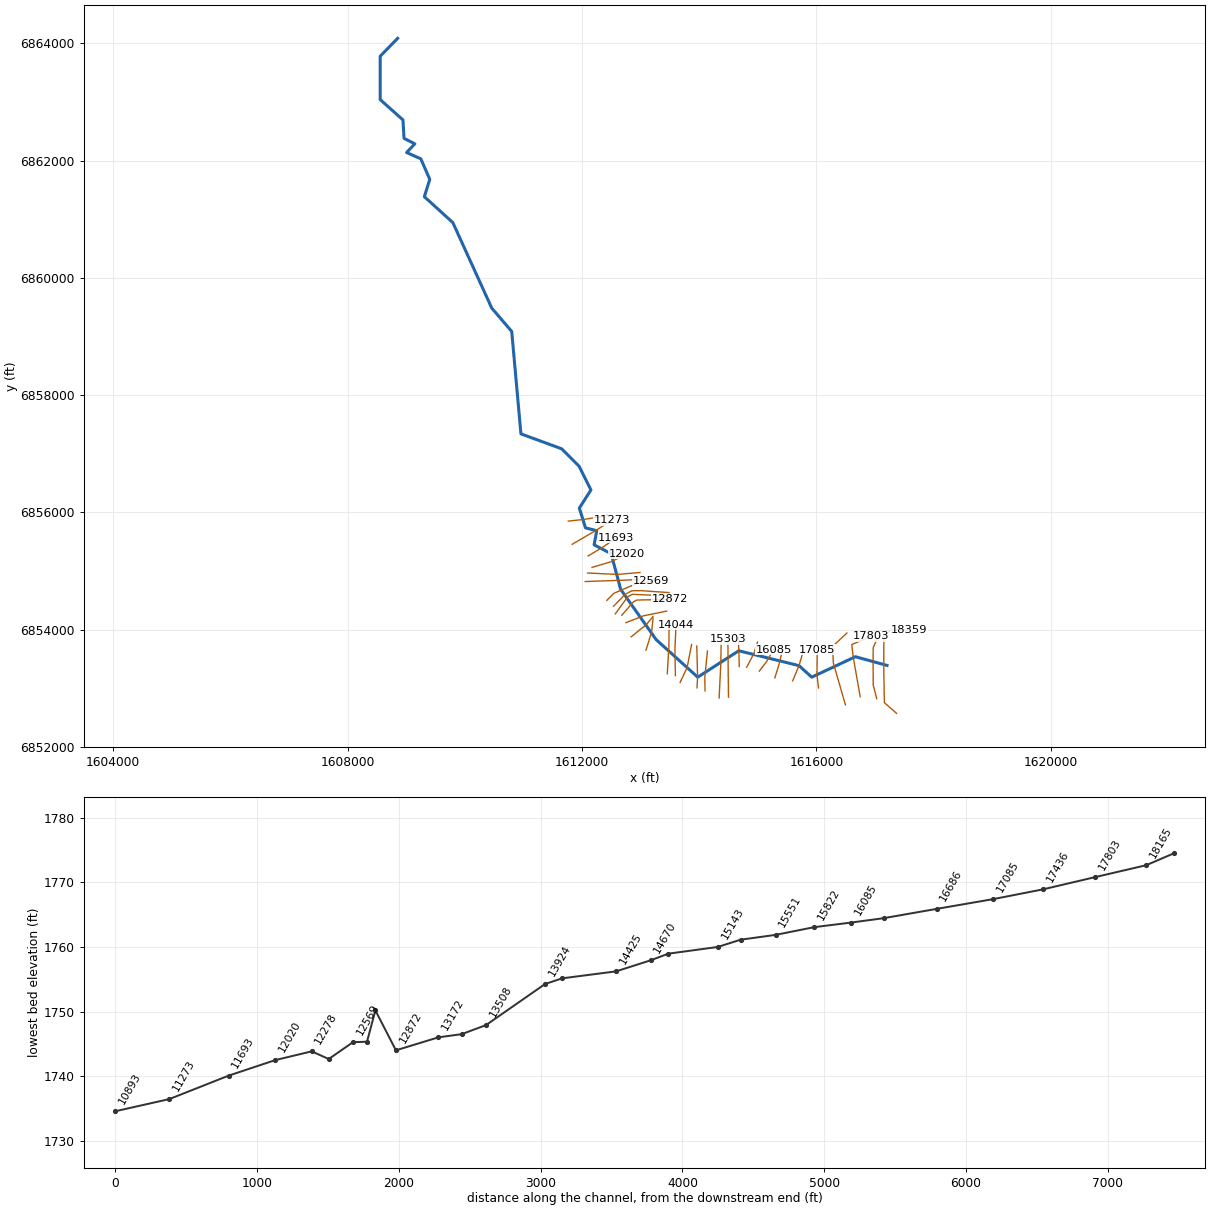
--- Elm 02 34.prj (project) ---

Proj Title=Elm 02 34 Base Level Engineering
Current Plan=p01
Default Exp/Contr=0.3,0.1
English Units
Geom File=g01
Flow File=f01
Plan File=p01
BEGIN DESCRIPTION:
Elm 02 34
END DESCRIPTION:

--- Elm 02 34.p01 (plan) ---

Plan Title=Multiple Run
Short Identifier=Multiple
Geom File=g01
Flow File=f01
Subcritical Flow
K Sum by GR= 0
Std Step Tol= 0.01
Critical Tol= 0.01
Num of Std Step Trials= 20
Max Error Tol= 0.3
Flow Tol Ratio= 0.001
Split Flow NTrial= 30
Split Flow Tol= 0.02
Split Flow Ratio= 0.02
Log Output Level= 0
Friction Slope Method= 1
Unsteady Friction Slope Method= 2
Unsteady Bridges Friction Slope Method= 1
Parabolic Critical Depth
Global Vel Dist=  1 , 1 , 1
Global Log Level= 0
CheckData=True
Encroach Param= -1, 0, 0, 0
BEGIN DESCRIPTION:
Multiple Run
END DESCRIPTION:

--- Elm 02 34.f01 (steady flow) ---

Flow Title=Multiple
Number of Profiles=7
Profile Names=10-year,25-year,50-year,1pct_min,100-year,1pct_plu,500-year
River Rch & RM= Elm 02 34,Reach-1,18359
      59      73      84      59      95     131     124
River Rch & RM= Elm 02 34,Reach-1,17803
     188     253     305     227     364     501     528
River Rch & RM= Elm 02 34,Reach-1,14794
     278     384     470     357     572     787     857
River Rch & RM= Elm 02 34,Reach-1,12020
     358     502     621     475     762    1050    1160
River Rch & RM= Elm 02 34,Reach-1,8780
     372     522     646     496     794    1090    1220
River Rch & RM= Elm 02 34,Reach-1,8197
     446     632     788     607     973    1340    1510
Boundary for River Rch & Prof#=Elm 02 34,Reach-1,1
Up Type=0
Dn Type=3
Dn Slope=0.001
Boundary for River Rch & Prof#=Elm 02 34,Reach-1,2
Up Type=0
Dn Type=3
Dn Slope=0.001
Boundary for River Rch & Prof#=Elm 02 34,Reach-1,3
Up Type=0
Dn Type=3
Dn Slope=0.001
Boundary for River Rch & Prof#=Elm 02 34,Reach-1,4
Up Type=0
Dn Type=3
Dn Slope=0.001
Boundary for River Rch & Prof#=Elm 02 34,Reach-1,5
Up Type=0
Dn Type=3
Dn Slope=0.001
Boundary for River Rch & Prof#=Elm 02 34,Reach-1,6
Up Type=0
Dn Type=3
Dn Slope=0.001
Boundary for River Rch & Prof#=Elm 02 34,Reach-1,7
Up Type=0
Dn Type=3
Dn Slope=0.001

--- Elm 02 34.g01 (geometry) ---

Geom Title=Existing Conditions

River Reach=Elm 02 34,Reach-1
Reach XY= 30
      1617205.00      6853388.00      1616665.51      6853536.78
      1615920.34      6853187.95      1615703.54      6853384.46
      1614674.98      6853638.04      1613974.99      6853187.94
      1613265.77      6853828.30      1612660.46      6854685.55
      1612497.31      6855294.48      1612207.50      6855446.15
      1612251.56      6855686.81      1612060.46      6855734.99
      1611955.24      6856072.78      1612152.86      6856382.03
      1611951.37      6856786.50      1611653.53      6857084.45
      1610958.53      6857339.46      1610801.38      6859086.50
      1610460.46      6859485.55      1609796.86      6860944.06
      1609310.61      6861385.69      1609403.18      6861681.88
      1609249.75      6862032.56      1609007.85      6862139.77
      1609148.03      6862288.23      1608964.01      6862380.94
      1608945.98      6862695.02      1608556.54      6863043.85
      1608556.97      6863782.35      1608855.00      6864088.00

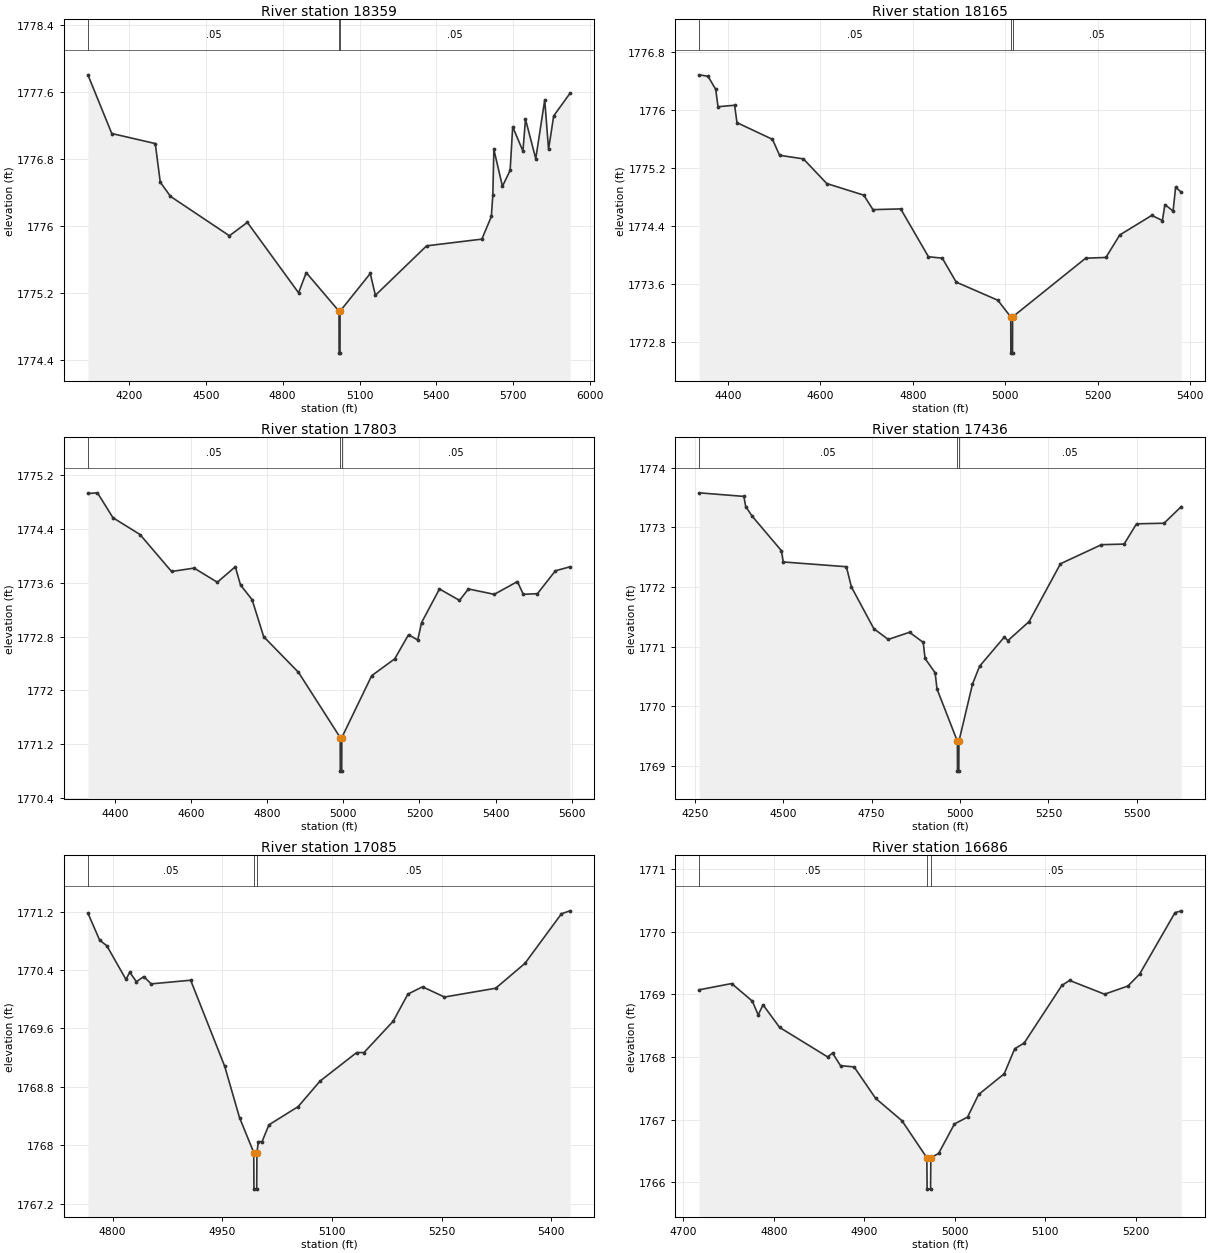
Type RM Length L Ch R = 1,18359,194,194,194
BEGIN DESCRIPTION:
Mapping XS 08e20f4a
END DESCRIPTION:
XS GIS Cut Line= 6
      1617368.29      6852570.01      1617159.94      6852752.31
      1617149.09      6853353.44      1617151.26      6853909.00
      1617283.64      6853987.12      1617578.78      6853995.80
#Sta/Elev= 30
  4039.4 1777.80  4132.6 1777.10  4302.5 1776.98  4321.9 1776.52  4361.9 1776.35
  4592.0 1775.88  4662.0 1776.04  4862.0 1775.20  4892.0 1775.44  5020.0 1774.98
  5020.3 1774.48  5023.8 1774.48  5024.0 1774.98  5142.0 1775.43  5162.0 1775.17
  5362.0 1775.76  5577.7 1775.84  5614.8 1776.11  5620.6 1776.37  5624.6 1776.91
  5658.1 1776.47  5688.1 1776.66  5698.1 1777.18  5738.1 1776.89  5748.1 1777.27
  5788.2 1776.80  5823.2 1777.50  5838.2 1776.91  5858.2 1777.31  5922.0 1777.58
#Mann=3,-1,0
  4039.4    0.05       0  5020.0    0.03       0  5024.0    0.05       0
Bank Sta=5020,5024
Exp/Cntr=0.3,0.1

Type RM Length L Ch R = 1,18165,362,362,362
BEGIN DESCRIPTION:
Elm 02 34 18164.96
END DESCRIPTION:
XS GIS Cut Line= 5
      1617029.03      6852819.44      1616970.20      6853051.24
      1616966.76      6853477.72      1616969.50      6853691.77
      1617036.87      6853840.29
#Sta/Elev= 30
  4338.0 1776.49  4357.1 1776.47  4373.7 1776.29  4378.8 1776.05  4414.6 1776.07
  4419.8 1775.83  4496.5 1775.60  4511.9 1775.38  4563.5 1775.33  4613.9 1774.99
  4693.9 1774.83  4713.9 1774.63  4773.9 1774.64  4833.9 1773.98  4863.9 1773.96
  4893.9 1773.63  4983.9 1773.38  5011.9 1773.15  5012.2 1772.65  5015.7 1772.65
  5015.9 1773.15  5173.9 1773.96  5217.7 1773.97  5247.6 1774.28  5316.8 1774.55
  5339.9 1774.48  5345.4 1774.70  5363.0 1774.61  5368.5 1774.94  5380.8 1774.87
#Mann=3,-1,0
  4338.0    0.05       0  5011.9   0.035       0  5015.9    0.05       0
Bank Sta=5011.9,5015.9
Exp/Cntr=0.3,0.1

Type RM Length L Ch R = 1,17803,367,367,367
BEGIN DESCRIPTION:
Elm 02 34 17802.87
END DESCRIPTION:
XS GIS Cut Line= 4
      1616747.57      6852853.18      1616630.39      6853517.22
      1616602.92      6853743.38      1616937.86      6853887.11
#Sta/Elev= 30
  4329.1 1774.93  4354.3 1774.94  4394.9 1774.57  4466.0 1774.32  4548.8 1773.77
  4608.2 1773.82  4669.1 1773.61  4716.3 1773.84  4730.0 1773.57  4760.5 1773.35
  4790.9 1772.80  4882.3 1772.27  4991.9 1771.30  4992.2 1770.80  4995.9 1770.80
  4996.2 1771.30  5074.7 1772.22  5135.1 1772.47  5171.5 1772.83  5195.6 1772.75
  5205.7 1773.01  5252.7 1773.51  5305.3 1773.34  5328.8 1773.51  5396.7 1773.43
  5457.5 1773.62  5472.9 1773.43  5510.1 1773.44  5557.2 1773.78  5595.7 1773.84
#Mann=3,-1,0
  4329.1    0.05       0  4991.9   0.035       0  4996.2    0.05       0
Bank Sta=4991.9,4996.2
Exp/Cntr=0.3,0.1

Type RM Length L Ch R = 1,17436,351,351,351
BEGIN DESCRIPTION:
Elm 02 34 17435.83
END DESCRIPTION:
XS GIS Cut Line= 4
      1616495.84      6852714.26      1616289.67      6853428.24
      1616273.83      6853710.04      1616520.65      6853941.27
#Sta/Elev= 30
  4262.2 1773.58  4388.6 1773.52  4393.8 1773.35  4411.8 1773.19  4494.7 1772.61
  4499.9 1772.42  4678.5 1772.34  4692.8 1772.00  4756.2 1771.30  4796.9 1771.12
  4857.1 1771.24  4895.9 1771.07  4901.1 1770.80  4929.6 1770.56  4934.8 1770.29
  4992.5 1769.41  4992.8 1768.91  4996.5 1768.91  4996.8 1769.41  5035.2 1770.37
  5055.2 1770.67  5125.3 1771.16  5135.3 1771.10  5195.4 1771.42  5284.1 1772.39
  5400.0 1772.71  5464.0 1772.72  5499.1 1773.06  5577.0 1773.07  5625.8 1773.35
#Mann=3,-1,0
  4262.2    0.05       0  4992.5   0.035       0  4996.8    0.05       0
Bank Sta=4992.5,4996.8
Exp/Cntr=0.3,0.1

Type RM Length L Ch R = 1,17085,399,399,399
BEGIN DESCRIPTION:
Elm 02 34 17085.42
END DESCRIPTION:
XS GIS Cut Line= 3
      1616036.16      6853002.13      1616009.02      6853234.38
      1616015.53      6853659.70
#Sta/Elev= 30
  4766.3 1771.18  4782.3 1770.81  4792.3 1770.73  4818.4 1770.27  4823.5 1770.37
  4832.6 1770.24  4842.7 1770.31  4852.8 1770.21  4906.8 1770.26  4953.4 1769.08
  4973.6 1768.38  4993.1 1767.90  4993.3 1767.40  4997.1 1767.40  4997.4 1767.90
  4999.4 1768.05  5004.4 1768.05  5013.8 1768.28  5053.8 1768.53  5083.8 1768.88
  5133.8 1769.27  5143.8 1769.27  5183.8 1769.70  5203.8 1770.07  5223.8 1770.17
  5253.8 1770.03  5323.8 1770.15  5363.8 1770.49  5413.8 1771.17  5425.5 1771.21
#Mann=3,-1,0
  4766.3    0.05       0  4993.1   0.035       0  4997.4    0.05       0
Bank Sta=4993.1,4997.4
Exp/Cntr=0.3,0.1

Type RM Length L Ch R = 1,16686,374,374,374
BEGIN DESCRIPTION:
Elm 02 34 16686.49
END DESCRIPTION:
XS GIS Cut Line= 3
      1615594.43      6853123.88      1615703.79      6853385.13
      1615773.61      6853624.75
#Sta/Elev= 30
  4717.5 1769.07  4753.4 1769.17  4776.2 1768.89  4782.7 1768.67  4788.1 1768.83
  4806.4 1768.47  4859.4 1768.00  4864.9 1768.06  4873.7 1767.86  4888.7 1767.84
  4912.4 1767.34  4941.7 1766.98  4969.1 1766.39  4969.4 1765.89  4973.2 1765.89
  4973.5 1766.39  4982.1 1766.46  4999.6 1766.93  5014.1 1767.04  5026.3 1767.40
  5054.6 1767.73  5066.2 1768.13  5076.6 1768.22  5118.3 1769.14  5126.8 1769.22
  5165.5 1769.00  5191.2 1769.13  5204.2 1769.32  5243.3 1770.30  5250.3 1770.33
#Mann=3,-1,0
  4717.5    0.05       0  4969.1    0.04       0  4973.5    0.05       0
Bank Sta=4969.1,4973.5
Exp/Cntr=0.3,0.1

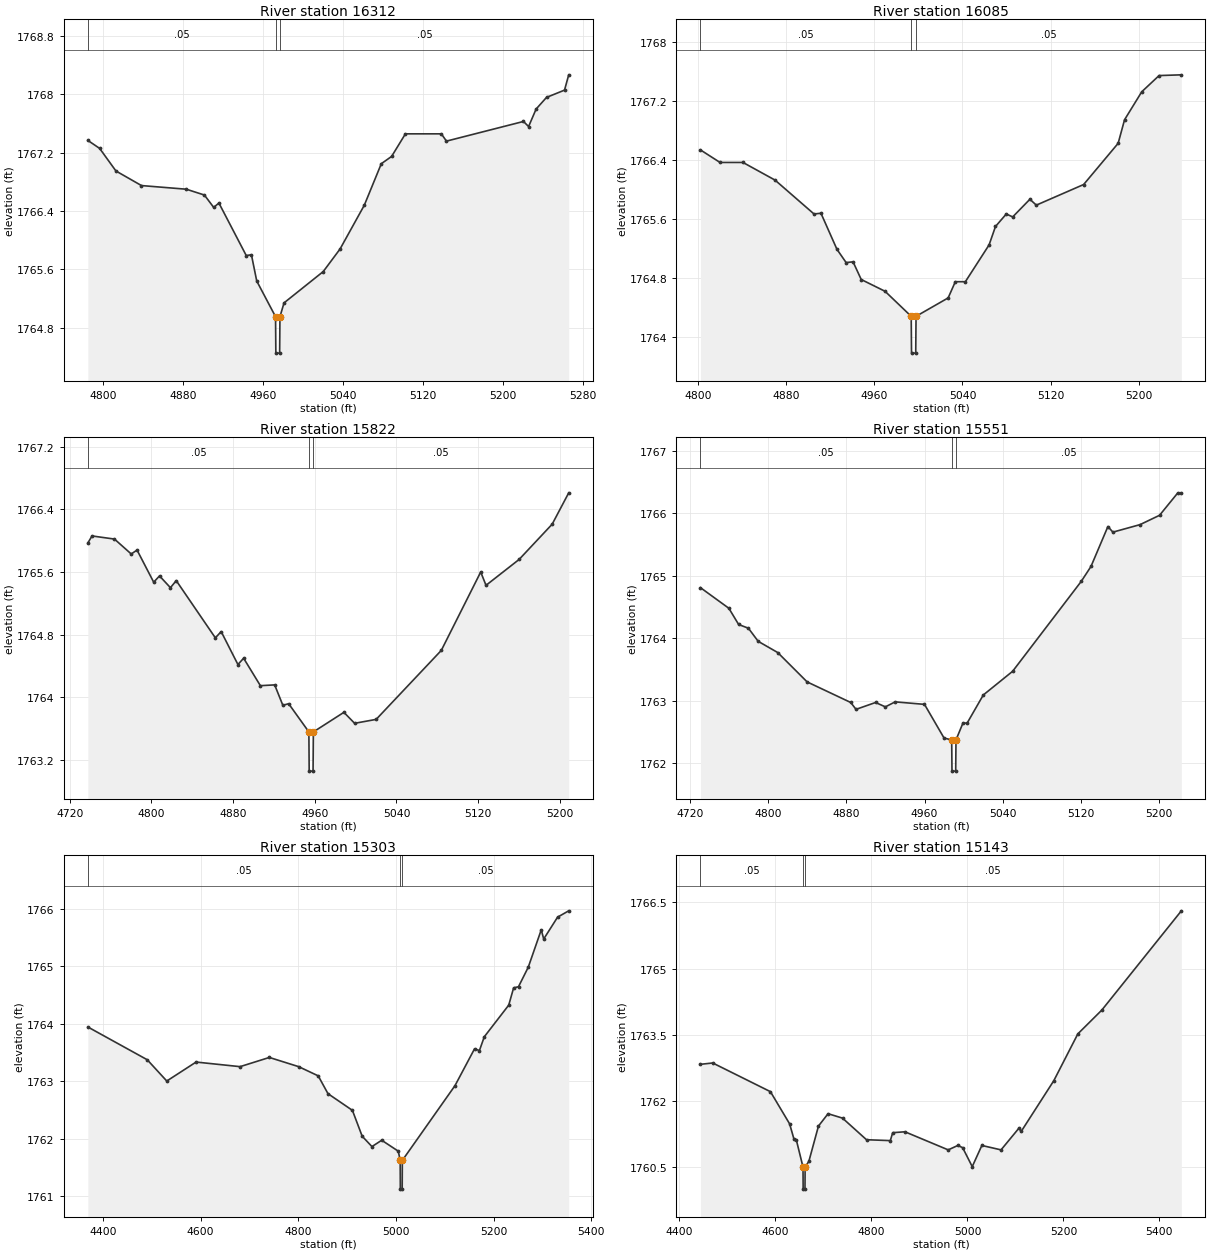
Type RM Length L Ch R = 1,16312,227,227,227
BEGIN DESCRIPTION:
Elm 02 34 16312.3
END DESCRIPTION:
XS GIS Cut Line= 3
      1615291.46      6853176.77      1615355.70      6853383.39
      1615420.40      6853639.57
#Sta/Elev= 30
  4785.0 1767.37  4796.8 1767.26  4813.1 1766.95  4838.6 1766.75  4883.4 1766.70
  4901.5 1766.62  4910.8 1766.45  4916.0 1766.51  4943.3 1765.79  4948.5 1765.80
  4953.8 1765.44  4972.6 1764.95  4972.9 1764.45  4976.7 1764.45  4977.0 1764.95
  4981.1 1765.14  5020.3 1765.57  5037.1 1765.88  5061.3 1766.48  5078.3 1767.05
  5088.6 1767.15  5102.4 1767.46  5138.3 1767.46  5143.4 1767.36  5220.4 1767.63
  5225.5 1767.56  5233.0 1767.80  5243.4 1767.96  5261.4 1768.06  5265.6 1768.27
#Mann=3,-1,0
  4785.0    0.05       0  4972.6   0.035       0  4977.0    0.05       0
Bank Sta=4972.6,4977
Exp/Cntr=0.3,0.1

Type RM Length L Ch R = 1,16085,263,263,263
BEGIN DESCRIPTION:
Elm 02 34 16084.5
END DESCRIPTION:
XS GIS Cut Line= 3
      1615026.79      6853292.18      1615146.14      6853448.43
      1615267.98      6853654.36
#Sta/Elev= 30
  4802.5 1766.54  4820.2 1766.37  4841.0 1766.37  4870.1 1766.13  4905.4 1765.67
  4911.7 1765.68  4926.2 1765.19  4934.5 1765.01  4940.8 1765.02  4948.2 1764.78
  4969.8 1764.62  4993.5 1764.28  4993.8 1763.78  4997.6 1763.78  4997.9 1764.28
  5027.0 1764.53  5033.5 1764.75  5042.6 1764.75  5064.1 1765.25  5069.9 1765.50
  5079.7 1765.67  5085.5 1765.63  5101.1 1765.87  5106.9 1765.79  5149.8 1766.07
  5181.1 1766.63  5186.9 1766.95  5202.5 1767.33  5218.2 1767.55  5238.4 1767.56
#Mann=3,-1,0
  4802.5    0.05       0  4993.5   0.035       0  4997.9    0.05       0
Bank Sta=4993.5,4997.9
Exp/Cntr=0.3,0.1

Type RM Length L Ch R = 1,15822,271,271,271
BEGIN DESCRIPTION:
Elm 02 34 15821.61
END DESCRIPTION:
XS GIS Cut Line= 3
      1614809.75      6853356.16      1614933.47      6853590.57
      1614995.33      6853787.01
#Sta/Elev= 30
  4737.7 1765.97  4741.8 1766.06  4763.8 1766.02  4780.2 1765.83  4785.9 1765.88
  4802.2 1765.47  4807.9 1765.55  4818.6 1765.40  4824.3 1765.49  4862.6 1764.76
  4868.3 1764.84  4884.7 1764.42  4890.3 1764.50  4906.7 1764.15  4920.7 1764.16
  4928.7 1763.90  4934.4 1763.92  4954.2 1763.56  4954.5 1763.06  4958.3 1763.06
  4958.6 1763.56  4988.5 1763.81  4999.0 1763.67  5020.1 1763.72  5083.9 1764.60
  5122.5 1765.60  5127.7 1765.43  5160.1 1765.76  5192.5 1766.21  5208.7 1766.61
#Mann=3,-1,0
  4737.7    0.05       0  4954.2   0.035       0  4958.6    0.05       0
Bank Sta=4954.2,4958.6
Exp/Cntr=0.3,0.1

Type RM Length L Ch R = 1,15551,248,248,248
BEGIN DESCRIPTION:
Elm 02 34 15551.32
END DESCRIPTION:
XS GIS Cut Line= 3
      1614683.90      6853369.04      1614676.96      6853641.57
      1614666.54      6853860.30
#Sta/Elev= 30
  4730.9 1764.81  4759.9 1764.48  4769.9 1764.22  4779.9 1764.16  4789.9 1763.95
  4809.9 1763.77  4839.9 1763.30  4884.5 1762.97  4889.9 1762.86  4909.9 1762.97
  4919.9 1762.90  4929.9 1762.98  4959.9 1762.94  4979.9 1762.40  4987.7 1762.37
  4988.0 1761.87  4991.8 1761.87  4992.1 1762.37  4999.2 1762.64  5003.5 1762.64
  5020.0 1763.09  5050.0 1763.47  5120.1 1764.91  5130.1 1765.15  5147.4 1765.79
  5152.5 1765.70  5180.2 1765.82  5200.2 1765.97  5218.9 1766.33  5222.5 1766.33
#Mann=3,-1,0
  4730.9    0.05       0  4987.7   0.035       0  4992.1    0.05       0
Bank Sta=4987.7,4992.1
Exp/Cntr=0.3,0.1

Type RM Length L Ch R = 1,15303,160,160,160
BEGIN DESCRIPTION:
Elm 02 34 15303.26
END DESCRIPTION:
XS GIS Cut Line= 3
      1614499.87      6852846.42      1614492.93      6853481.85
      1614489.46      6853830.77
#Sta/Elev= 30
  4369.2 1763.94  4490.8 1763.37  4530.8 1763.00  4590.8 1763.33  4680.8 1763.25
  4740.8 1763.41  4800.8 1763.25  4840.8 1763.09  4860.8 1762.78  4910.8 1762.49
  4930.8 1762.04  4950.8 1761.86  4970.8 1761.97  5004.7 1761.78  5008.6 1761.62
  5008.9 1761.12  5012.7 1761.12  5013.0 1761.62  5120.8 1762.92  5160.8 1763.56
  5170.8 1763.53  5180.8 1763.77  5230.8 1764.32  5240.8 1764.62  5250.8 1764.64
  5270.8 1764.98  5297.4 1765.63  5302.4 1765.47  5330.8 1765.85  5353.6 1765.96
#Mann=3,-1,0
  4369.2    0.05       0  5008.6   0.035       0  5013.0    0.05       0
Bank Sta=5008.6,5013
Exp/Cntr=0.3,0.1

Type RM Length L Ch R = 1,15143,349,349,349
BEGIN DESCRIPTION:
Elm 02 34 15143.26
END DESCRIPTION:
XS GIS Cut Line= 3
      1614340.15      6852832.51      1614367.93      6853391.57
      1614376.60      6853833.63
#Sta/Elev= 30
  4443.8 1762.83  4469.3 1762.86  4589.5 1762.21  4629.5 1761.48  4638.4 1761.14
  4643.4 1761.12  4657.4 1760.50  4657.7 1760.00  4661.5 1760.00  4661.8 1760.50
  4669.6 1760.63  4689.6 1761.43  4709.6 1761.71  4739.7 1761.61  4789.7 1761.12
  4839.3 1761.10  4844.3 1761.28  4869.8 1761.30  4959.9 1760.89  4980.0 1760.99
  4990.0 1760.94  5010.0 1760.51  5030.0 1760.99  5070.0 1760.89  5107.1 1761.38
  5112.1 1761.31  5180.0 1762.46  5230.0 1763.52  5280.0 1764.06  5445.7 1766.31
#Mann=3,-1,0
  4443.8    0.05       0  4657.4   0.035       0  4661.8    0.05       0
Bank Sta=4657.4,4661.8
Exp/Cntr=0.3,0.1

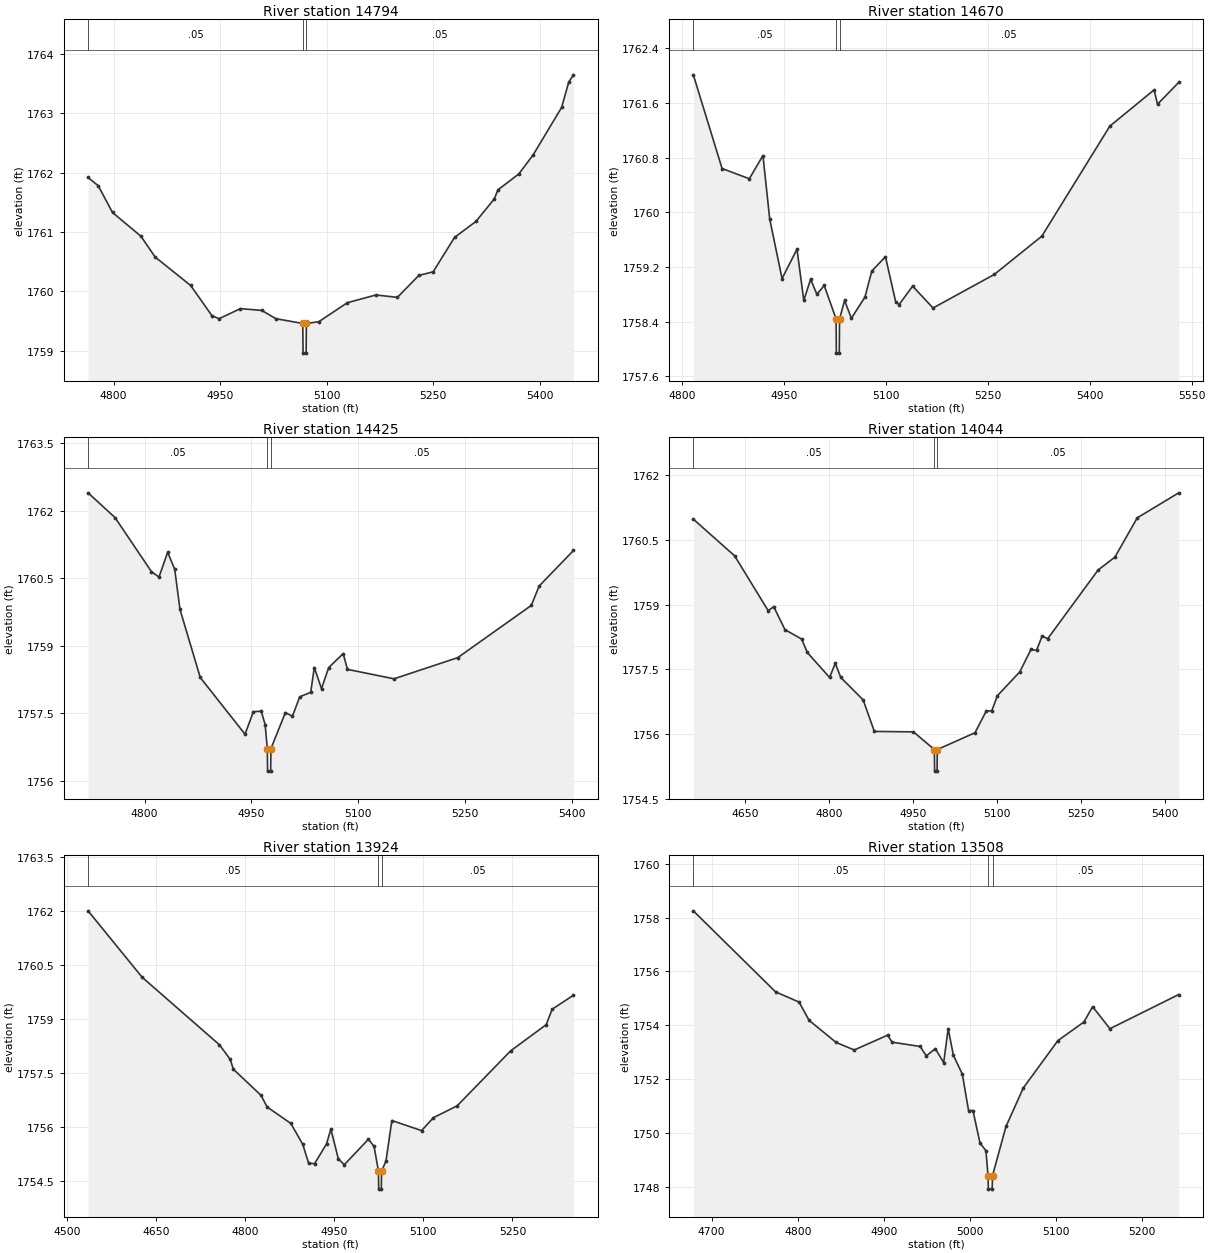
Type RM Length L Ch R = 1,14794,124,124,124
BEGIN DESCRIPTION:
Elm 02 34 14793.77
END DESCRIPTION:
XS GIS Cut Line= 3
      1614099.68      6852953.63      1614096.20      6853191.53
      1614141.19      6853634.53
#Sta/Elev= 30
  4764.0 1761.92  4778.4 1761.78  4798.4 1761.33  4838.4 1760.93  4858.4 1760.58
  4908.4 1760.10  4938.4 1759.59  4948.4 1759.54  4978.4 1759.71  5008.4 1759.68
  5028.5 1759.54  5066.2 1759.46  5066.6 1758.96  5070.9 1758.96  5071.3 1759.46
  5088.8 1759.49  5129.0 1759.81  5169.2 1759.94  5199.4 1759.90  5229.6 1760.27
  5249.7 1760.33  5279.8 1760.91  5310.0 1761.18  5335.8 1761.56  5340.8 1761.71
  5370.3 1761.98  5390.4 1762.30  5430.5 1763.10  5440.6 1763.53  5447.2 1763.65
#Mann=3,-1,0
  4764.0    0.05       0  5066.2   0.035       0  5071.3    0.05       0
Bank Sta=5066.2,5071.3
Exp/Cntr=0.3,0.1

Type RM Length L Ch R = 1,14670,245,245,245
BEGIN DESCRIPTION:
Elm 02 34 14670.1
END DESCRIPTION:
XS GIS Cut Line= 3
      1613962.52      6853005.77      1613972.94      6853191.53
      1613959.05      6853719.30
#Sta/Elev= 30
  4817.0 1762.01  4859.3 1760.64  4899.4 1760.49  4919.4 1760.83  4929.4 1759.90
  4947.5 1759.03  4969.5 1759.46  4979.5 1758.71  4989.5 1759.02  4998.8 1758.80
  5009.5 1758.93  5027.0 1758.44  5027.4 1757.94  5031.7 1757.94  5032.1 1758.44
  5039.5 1758.71  5049.5 1758.45  5069.5 1758.76  5079.5 1759.14  5099.6 1759.35
  5114.7 1758.69  5119.7 1758.65  5139.6 1758.92  5169.6 1758.60  5259.6 1759.09
  5329.6 1759.65  5429.7 1761.26  5494.8 1761.79  5499.8 1761.58  5531.0 1761.90
#Mann=3,-1,0
  4817.0    0.05       0  5027.0    0.05       0  5032.1    0.05       0
Bank Sta=5027,5032.1
Exp/Cntr=0.3,0.1

Type RM Length L Ch R = 1,14425,381,381,381
BEGIN DESCRIPTION:
Elm 02 34 14425.19
END DESCRIPTION:
XS GIS Cut Line= 3
      1613674.34      6853097.80      1613794.12      6853352.99
      1613870.50      6853745.32
#Sta/Elev= 30
  4720.6 1762.40  4758.5 1761.85  4809.6 1760.65  4820.2 1760.53  4832.4 1761.08
  4842.3 1760.70  4849.7 1759.81  4878.1 1758.30  4941.0 1757.04  4952.8 1757.54
  4963.8 1757.55  4969.3 1757.25  4972.3 1756.72  4972.7 1756.22  4977.0 1756.22
  4977.4 1756.72  4997.7 1757.52  5007.6 1757.44  5017.8 1757.87  5033.2 1757.97
  5038.3 1758.52  5048.4 1758.05  5058.5 1758.52  5078.9 1758.83  5084.8 1758.48
  5150.2 1758.27  5239.7 1758.74  5343.0 1759.90  5354.0 1760.33  5402.2 1761.12
#Mann=3,-1,0
  4720.6    0.05       0  4972.3   0.035       0  4977.4    0.05       0
Bank Sta=4972.3,4977.4
Exp/Cntr=0.3,0.1

Type RM Length L Ch R = 1,14044,120,120,120
BEGIN DESCRIPTION:
Elm 02 34 14043.53
END DESCRIPTION:
XS GIS Cut Line= 3
      1613594.47      6853214.14      1613585.79      6853660.28
      1613604.88      6854082.12
#Sta/Elev= 30
  4556.8 1760.98  4630.7 1760.13  4690.7 1758.86  4700.7 1758.95  4720.7 1758.42
  4750.7 1758.20  4760.7 1757.89  4800.7 1757.31  4810.7 1757.64  4820.7 1757.31
  4860.7 1756.79  4880.7 1756.06  4950.7 1756.05  4988.1 1755.64  4988.5 1755.14
  4992.9 1755.14  4993.3 1755.64  5060.8 1756.03  5080.8 1756.53  5090.8 1756.54
  5101.0 1756.89  5140.9 1757.44  5160.9 1757.96  5170.9 1757.94  5180.9 1758.27
  5190.9 1758.21  5281.0 1759.80  5311.1 1760.10  5351.1 1761.01  5425.3 1761.59
#Mann=3,-1,0
  4556.8    0.05       0  4988.1   0.035       0  4993.3    0.05       0
Bank Sta=4988.1,4993.3
Exp/Cntr=0.3,0.1

Type RM Length L Ch R = 1,13924,416,416,416
BEGIN DESCRIPTION:
Elm 02 34 13923.77
END DESCRIPTION:
XS GIS Cut Line= 3
      1613455.58      6853247.06      1613483.36      6853714.10
      1613486.82      6854063.91
#Sta/Elev= 30
  4535.1 1762.01  4626.2 1760.16  4756.4 1758.28  4774.7 1757.87  4779.8 1757.60
  4826.6 1756.87  4836.6 1756.55  4876.6 1756.09  4896.7 1755.51  4906.7 1754.98
  4916.7 1754.97  4936.8 1755.52  4944.1 1755.93  4956.8 1755.10  4966.8 1754.94
  5007.4 1755.65  5016.9 1755.45  5024.3 1754.76  5024.7 1754.26  5029.1 1754.26
  5029.5 1754.76  5036.9 1755.04  5046.9 1756.17  5096.9 1755.89  5116.9 1756.25
  5156.9 1756.58  5246.9 1758.11  5306.9 1758.84  5316.9 1759.27  5352.8 1759.66
#Mann=3,-1,0
  4535.1    0.05       0  5024.3    0.05       0  5029.5    0.05       0
Bank Sta=5024.3,5029.5
Exp/Cntr=0.3,0.1

Type RM Length L Ch R = 1,13508,172,172,172
BEGIN DESCRIPTION:
Elm 02 34 13507.72
END DESCRIPTION:
XS GIS Cut Line= 3
      1613092.35      6853649.57      1613187.83      6853956.61
      1613213.87      6854197.46
#Sta/Elev= 30
  4678.7 1758.25  4774.2 1755.24  4801.5 1754.86  4813.2 1754.18  4844.6 1753.36
  4865.6 1753.08  4904.4 1753.63  4909.6 1753.37  4942.2 1753.21  4949.3 1752.86
  4959.8 1753.13  4969.5 1752.61  4974.7 1753.87  4980.8 1752.88  4991.2 1752.18
  4998.4 1750.83  5003.5 1750.83  5011.7 1749.62  5018.6 1749.34  5021.0 1748.41
  5021.4 1747.91  5025.8 1747.91  5026.2 1748.41  5041.9 1750.24  5062.0 1751.67
  5102.2 1753.43  5132.4 1754.12  5142.5 1754.69  5162.6 1753.87  5242.5 1755.14
#Mann=3,-1,0
  4678.7    0.05       0  5021.0    0.05       0  5026.2    0.05       0
Bank Sta=5021,5026.2
Exp/Cntr=0.3,0.1

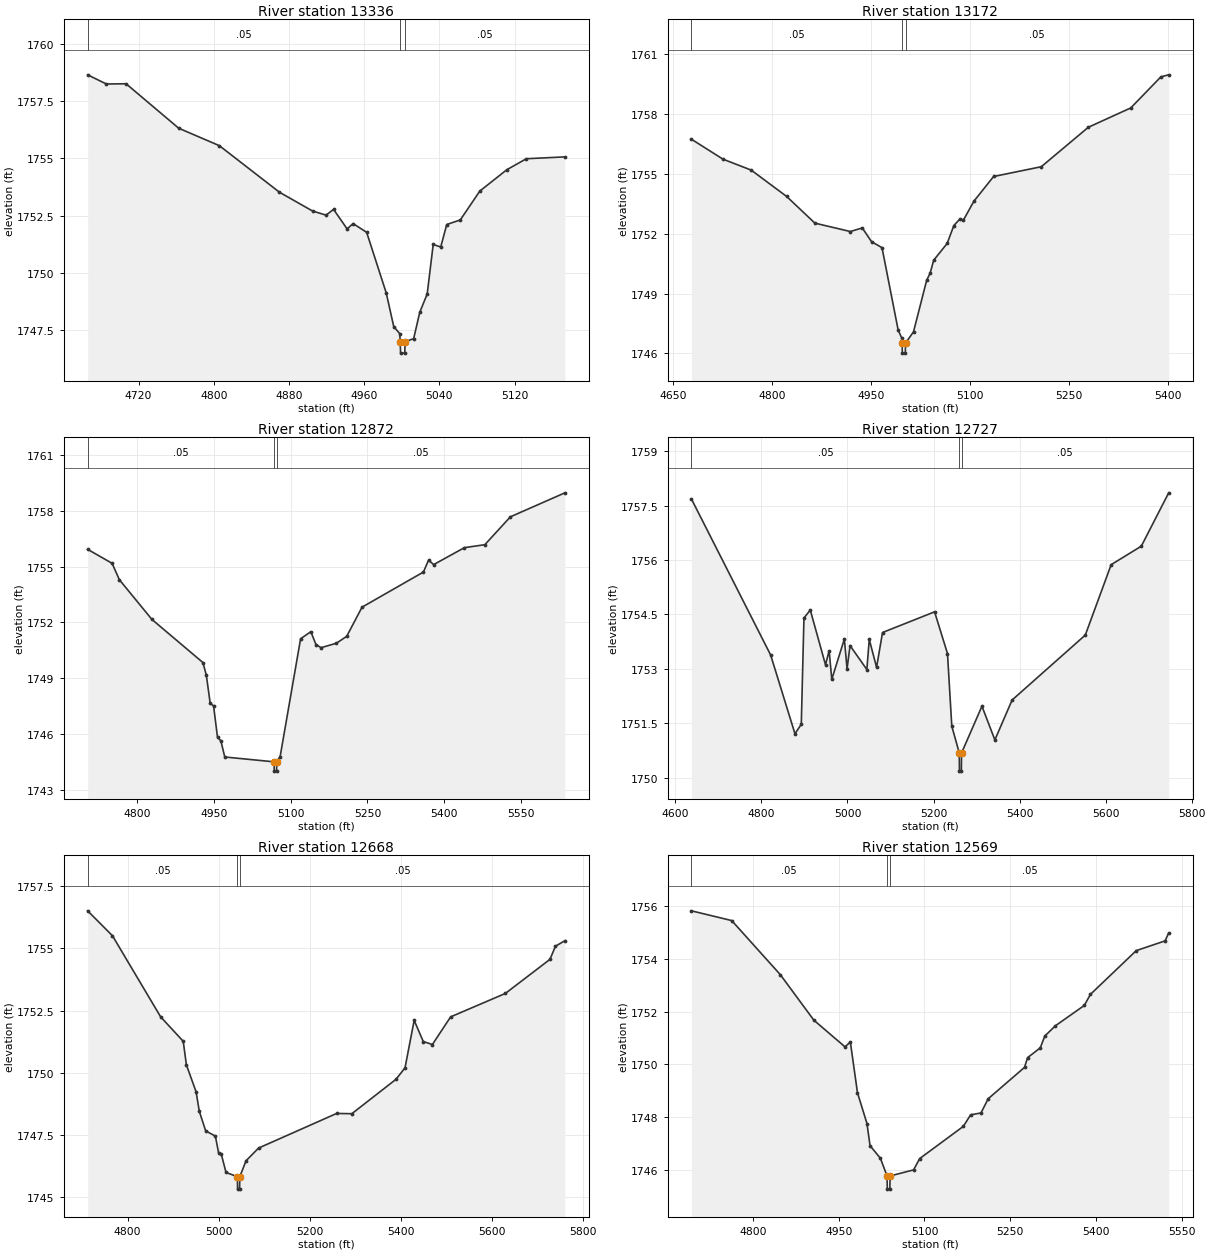
Type RM Length L Ch R = 1,13336,164,164,164
BEGIN DESCRIPTION:
Elm 02 34 13336.28
END DESCRIPTION:
XS GIS Cut Line= 3
      1612839.50      6853876.30      1613101.02      6854086.82
      1613209.51      6854220.26
#Sta/Elev= 30
  4665.8 1758.64  4685.7 1758.24  4706.7 1758.25  4762.7 1756.31  4805.9 1755.55
  4869.8 1753.52  4905.0 1752.70  4919.4 1752.52  4927.4 1752.77  4941.8 1751.92
  4948.2 1752.15  4962.6 1751.77  4983.4 1749.13  4991.4 1747.66  4997.8 1747.35
  4998.3 1747.00  4998.7 1746.50  5003.1 1746.50  5003.5 1747.00  5012.6 1747.13
  5019.1 1748.28  5027.0 1749.08  5033.4 1751.24  5041.4 1751.13  5047.8 1752.11
  5062.2 1752.31  5083.0 1753.57  5111.7 1754.50  5132.5 1754.98  5173.5 1755.06
#Mann=3,-1,0
  4665.8    0.05       0  4998.3    0.05       0  5003.5    0.05       0
Bank Sta=4998.3,5003.5
Exp/Cntr=0.3,0.1

Type RM Length L Ch R = 1,13172,300,300,300
BEGIN DESCRIPTION:
Elm 02 34 13171.91
END DESCRIPTION:
XS GIS Cut Line= 3
      1612750.44      6854118.13      1613051.26      6854235.33
      1613444.48      6854314.76
#Sta/Elev= 30
  4677.5 1756.74  4725.3 1755.74  4768.2 1755.19  4821.9 1753.87  4864.8 1752.53
  4918.5 1752.11  4936.7 1752.29  4950.7 1751.60  4966.6 1751.30  4991.1 1747.17
  4996.5 1746.77  4997.1 1746.51  4997.5 1746.01  5001.9 1746.01  5002.3 1746.51
  5014.4 1747.08  5034.4 1749.67  5039.5 1750.01  5045.0 1750.67  5065.4 1751.51
  5075.6 1752.41  5085.1 1752.75  5090.2 1752.69  5106.2 1753.64  5135.9 1754.87
  5208.2 1755.36  5279.6 1757.34  5344.0 1758.31  5389.7 1759.87  5401.5 1759.97
#Mann=3,-1,0
  4677.5    0.05       0  4997.1    0.05       0  5002.3    0.05       0
Bank Sta=4997.1,5002.3
Exp/Cntr=0.3,0.1

Type RM Length L Ch R = 1,12872,145,145,145
BEGIN DESCRIPTION:
Elm 02 34 12871.91
END DESCRIPTION:
XS GIS Cut Line= 4
      1612680.02      6854245.50      1612876.23      6854471.23
      1612937.00      6854504.21      1613501.47      6854514.60
#Sta/Elev= 30
  4703.2 1755.93  4750.9 1755.18  4765.1 1754.30  4828.8 1752.16  4928.5 1749.84
  4935.1 1749.17  4942.7 1747.65  4949.3 1747.51  4957.0 1745.82  4963.6 1745.63
  4971.2 1744.76  5067.5 1744.50  5068.0 1744.00  5072.4 1744.00  5072.8 1744.50
  5079.4 1744.78  5119.4 1751.12  5139.4 1751.50  5149.4 1750.81  5159.4 1750.64
  5189.4 1750.88  5209.5 1751.25  5239.5 1752.82  5359.5 1754.71  5369.5 1755.35
  5379.5 1755.11  5439.5 1756.02  5479.5 1756.18  5529.5 1757.68  5636.0 1758.97
#Mann=3,-1,0
  4703.2    0.05       0  5067.5    0.05       0  5072.8    0.05       0
Bank Sta=5067.5,5072.8
Exp/Cntr=0.3,0.1

Type RM Length L Ch R = 1,12727,59,59,59
BEGIN DESCRIPTION:
Elm 02 34 12727.47
END DESCRIPTION:
XS GIS Cut Line= 5
      1612568.93      6854268.08      1612728.66      6854488.59
      1612784.22      6854563.24      1612862.34      6854601.43
      1613518.58      6854571.92
#Sta/Elev= 30
  4637.4 1757.68  4821.5 1753.38  4878.0 1751.21  4892.7 1751.47  4898.9 1754.40
  4913.6 1754.62  4949.0 1753.11  4957.4 1753.50  4963.6 1752.71  4992.8 1753.82
  4999.1 1753.00  5006.0 1753.64  5045.1 1752.98  5050.7 1753.81  5067.7 1753.04
  5081.5 1754.00  5202.5 1754.57  5232.5 1753.42  5242.5 1751.42  5259.9 1750.68
  5260.3 1750.18  5264.7 1750.18  5265.2 1750.68  5312.6 1751.97  5342.6 1751.04
  5382.7 1752.14  5552.8 1753.93  5612.9 1755.87  5683.0 1756.38  5746.6 1757.85
#Mann=3,-1,0
  4637.4    0.05       0  5259.9    0.05       0  5265.2    0.05       0
Bank Sta=5259.9,5265.2
Exp/Cntr=0.3,0.1

Type RM Length L Ch R = 1,12668,99,99,99
BEGIN DESCRIPTION:
Elm 02 34 12668.15
END DESCRIPTION:
XS GIS Cut Line= 5
      1612537.67      6854398.28      1612740.82      6854603.17
      1612851.93      6854662.20      1613002.97      6854663.93
      1613485.65      6854630.95
#Sta/Elev= 30
  4712.1 1756.51  4766.6 1755.51  4872.6 1752.25  4922.2 1751.27  4929.2 1750.32
  4950.5 1749.24  4957.5 1748.46  4971.6 1747.67  4992.9 1747.46  4999.9 1746.79
  5005.8 1746.74  5016.3 1746.00  5041.3 1745.83  5041.7 1745.33  5046.1 1745.33
  5046.6 1745.83  5060.3 1746.47  5087.9 1746.98  5259.5 1748.37  5292.9 1748.36
  5389.8 1749.74  5409.8 1750.20  5429.9 1752.11  5449.9 1751.26  5470.0 1751.14
  5510.1 1752.25  5630.3 1753.19  5728.4 1754.56  5740.6 1755.09  5761.3 1755.31
#Mann=3,-1,0
  4712.1    0.05       0  5041.3    0.05       0  5046.6    0.05       0
Bank Sta=5041.3,5046.6
Exp/Cntr=0.3,0.1

Type RM Length L Ch R = 1,12569,171,171,171
BEGIN DESCRIPTION:
Mapping XS 4db39168
END DESCRIPTION:
XS GIS Cut Line= 4
      1612425.16      6854498.17      1612542.34      6854617.95
      1612948.59      6854792.43      1613171.28      6854820.91
#Sta/Elev= 30
  4692.7 1755.82  4763.1 1755.45  4848.0 1753.40  4906.7 1751.67  4961.1 1750.66
  4970.5 1750.84  4982.9 1748.92  4999.5 1747.75  5004.9 1746.91  5023.0 1746.43
  5034.6 1745.76  5035.1 1745.26  5039.5 1745.26  5039.9 1745.76  5081.0 1745.99
  5091.7 1746.42  5167.9 1747.64  5180.7 1748.08  5198.8 1748.15  5211.4 1748.69
  5274.9 1749.88  5280.3 1750.25  5302.4 1750.62  5310.4 1751.07  5329.0 1751.46
  5379.4 1752.23  5390.1 1752.65  5470.2 1754.31  5520.6 1754.68  5526.9 1754.98
#Mann=3,-1,0
  4692.7    0.05       0  5034.6    0.05       0  5039.9    0.05       0
Bank Sta=5034.6,5039.9
Exp/Cntr=0.3,0.1

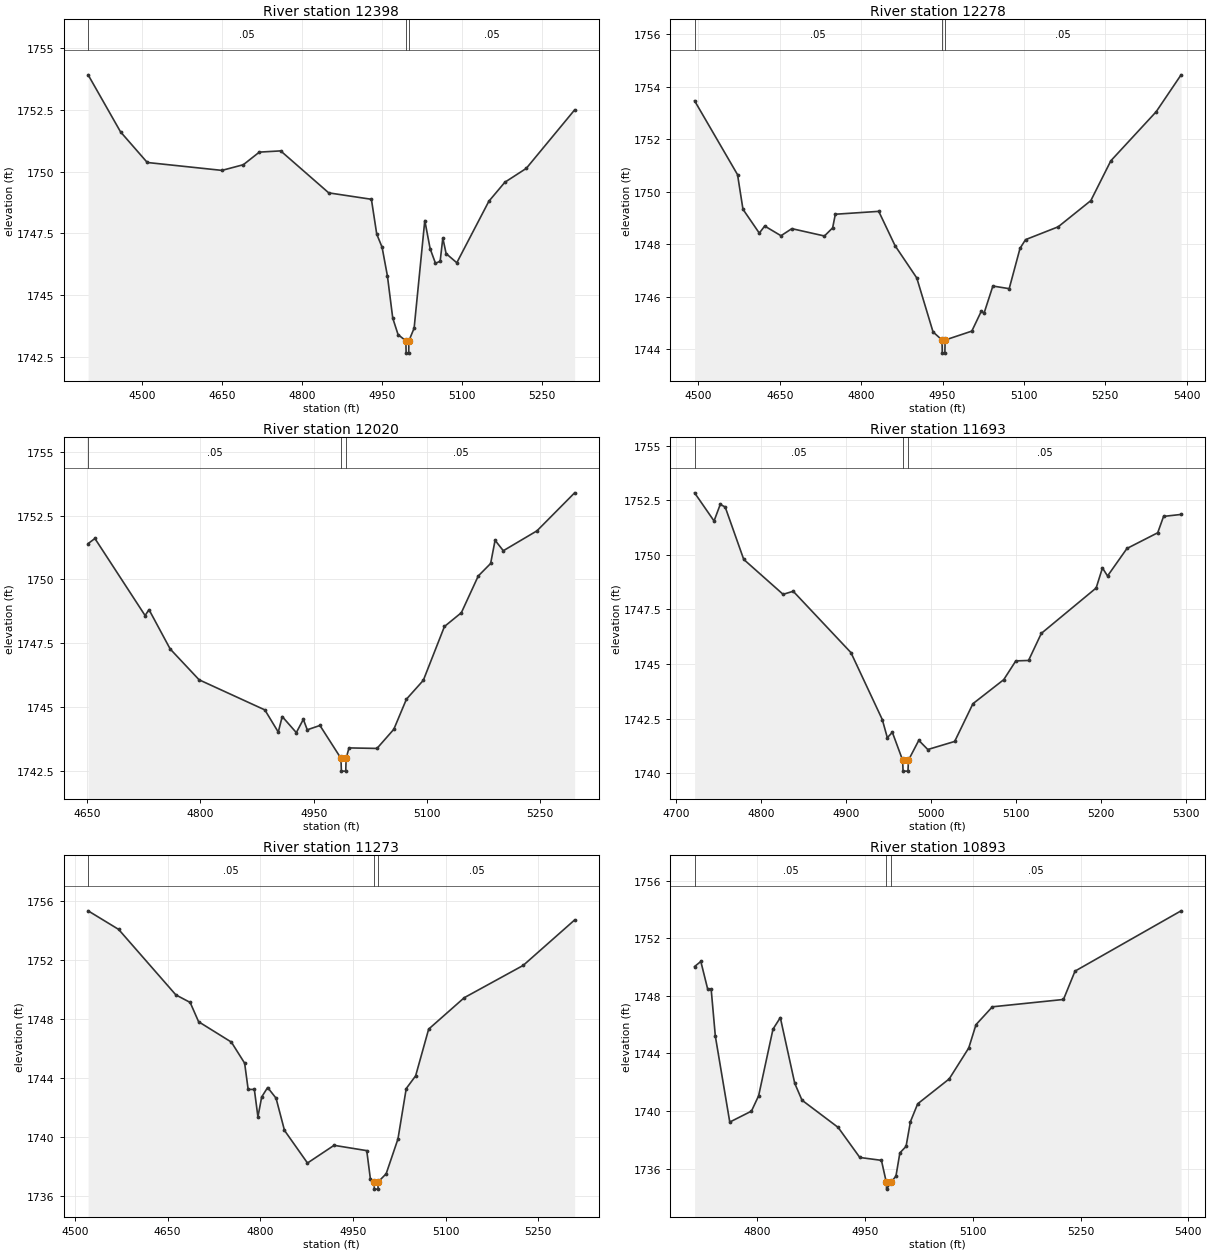
Type RM Length L Ch R = 1,12398,120,120,120
BEGIN DESCRIPTION:
Elm 02 34 12397.68
END DESCRIPTION:
XS GIS Cut Line= 3
      1612054.20      6854819.37      1612654.85      6854840.20
      1612965.63      6854854.09
#Sta/Elev= 30
  4398.5 1753.92  4459.3 1751.61  4509.4 1750.37  4649.4 1750.05  4689.5 1750.28
  4719.5 1750.79  4759.5 1750.84  4849.6 1749.14  4929.6 1748.88  4939.6 1747.47
  4949.6 1746.94  4959.6 1745.78  4969.6 1744.07  4979.6 1743.40  4994.2 1743.15
  4994.7 1742.65  4999.5 1742.65  4999.9 1743.15  5009.7 1743.66  5029.7 1748.02
  5039.7 1746.88  5049.7 1746.29  5058.5 1746.37  5063.5 1747.31  5069.7 1746.68
  5089.7 1746.31  5149.8 1748.80  5179.8 1749.57  5219.9 1750.13  5310.6 1752.50
#Mann=3,-1,0
  4398.5    0.05       0  4994.2    0.05       0  4999.9    0.05       0
Bank Sta=4994.2,4999.9
Exp/Cntr=0.3,0.1

Type RM Length L Ch R = 1,12278,258,258,258
BEGIN DESCRIPTION:
Elm 02 34 12277.65
END DESCRIPTION:
XS GIS Cut Line= 3
      1612095.87      6854965.19      1612602.77      6854940.89
      1612990.80      6854973.80
#Sta/Elev= 30
  4492.9 1753.47  4572.1 1750.65  4582.1 1749.33  4612.2 1748.42  4622.2 1748.69
  4652.2 1748.32  4672.2 1748.59  4732.3 1748.31  4747.4 1748.62  4752.4 1749.14
  4832.4 1749.25  4862.5 1747.94  4902.5 1746.71  4932.5 1744.65  4949.1 1744.34
  4949.5 1743.84  4954.3 1743.84  4954.8 1744.34  5004.0 1744.68  5021.5 1745.44
  5026.5 1745.36  5042.8 1746.40  5072.9 1746.30  5092.9 1747.84  5103.0 1748.17
  5163.2 1748.66  5223.4 1749.66  5260.3 1751.18  5343.8 1753.05  5389.8 1754.46
#Mann=3,-1,0
  4492.9    0.05       0  4949.1    0.05       0  4954.8    0.05       0
Bank Sta=4949.1,4954.8
Exp/Cntr=0.3,0.1

Type RM Length L Ch R = 1,12020,327,327,327
BEGIN DESCRIPTION:
Elm 02 34 12020.36
END DESCRIPTION:
XS GIS Cut Line= 3
      1612170.49      6855060.69      1612503.81      6855159.64
      1612769.11      6855293.16
#Sta/Elev= 30
  4651.1 1751.40  4660.1 1751.60  4726.6 1748.58  4731.8 1748.81  4759.8 1747.27
  4798.2 1746.06  4885.3 1744.88  4903.1 1744.01  4908.3 1744.62  4927.0 1743.99
  4936.3 1744.51  4941.5 1744.10  4958.3 1744.27  4986.2 1742.98  4986.7 1742.48
  4992.5 1742.48  4993.0 1742.98  4996.8 1743.39  5033.9 1743.37  5056.2 1744.12
  5072.9 1745.30  5095.3 1746.04  5123.3 1748.15  5145.7 1748.69  5168.1 1750.13
  5184.5 1750.62  5190.4 1751.53  5201.3 1751.12  5245.9 1751.90  5295.8 1753.39
#Mann=3,-1,0
  4651.1    0.05       0  4986.2    0.05       0  4993.0    0.05       0
Bank Sta=4986.2,4993
Exp/Cntr=0.3,0.1

Type RM Length L Ch R = 1,11693,420,420,420
BEGIN DESCRIPTION:
Elm 02 34 11692.65
END DESCRIPTION:
XS GIS Cut Line= 3
      1612105.34      6855256.82      1612341.86      6855397.86
      1612587.83      6855564.00
#Sta/Elev= 30
  4721.8 1752.84  4744.7 1751.55  4752.0 1752.31  4757.8 1752.19  4779.6 1749.79
  4825.9 1748.19  4837.8 1748.33  4905.7 1745.52  4942.6 1742.45  4948.5 1741.62
  4954.4 1741.87  4966.5 1740.59  4967.0 1740.09  4972.8 1740.09  4973.3 1740.59
  4985.5 1741.50  4996.1 1741.08  5027.7 1741.45  5049.2 1743.18  5085.4 1744.28
  5099.6 1745.14  5114.6 1745.16  5129.6 1746.40  5194.1 1748.48  5201.5 1749.40
  5207.5 1749.03  5230.3 1750.29  5266.5 1751.01  5273.4 1751.76  5294.0 1751.85
#Mann=3,-1,0
  4721.8    0.05       0  4966.5    0.05       0  4973.3    0.05       0
Bank Sta=4966.5,4973.3
Exp/Cntr=0.3,0.1

Type RM Length L Ch R = 1,11273,380,380,380
BEGIN DESCRIPTION:
Elm 02 34 11272.89
END DESCRIPTION:
XS GIS Cut Line= 3
      1611832.35      6855454.74      1612248.98      6855697.78
      1612504.83      6855863.74
#Sta/Elev= 30
  4521.5 1755.32  4570.9 1754.06  4663.5 1749.62  4686.6 1749.11  4700.3 1747.80
  4753.3 1746.42  4774.8 1744.99  4780.5 1743.21  4790.5 1743.21  4796.3 1741.35
  4802.4 1742.70  4812.0 1743.34  4825.6 1742.62  4839.3 1740.43  4876.5 1738.22
  4919.5 1739.42  4972.4 1739.06  4978.2 1737.17  4984.2 1736.95  4984.7 1736.45
  4990.6 1736.45  4991.1 1736.95  5003.8 1737.49  5022.9 1739.85  5036.3 1743.27
  5051.5 1744.13  5072.6 1747.30  5130.2 1749.43  5225.6 1751.62  5308.8 1754.70
#Mann=3,-1,0
  4521.5    0.05       0  4984.2    0.05       0  4991.1    0.05       0
Bank Sta=4984.2,4991.1
Exp/Cntr=0.3,0.1

Type RM Length L Ch R = 1,10893,318,318,318
BEGIN DESCRIPTION:
Elm 02 34 10893.3
END DESCRIPTION:
XS GIS Cut Line= 3
      1611766.31      6855850.55      1612051.06      6855881.81
      1612436.49      6855947.78
#Sta/Elev= 30
  4712.4 1750.04  4721.1 1750.39  4730.5 1748.50  4735.5 1748.46  4741.3 1745.20
  4761.4 1739.23  4791.6 1739.99  4801.6 1741.06  4821.6 1745.69  4831.8 1746.49
  4851.9 1741.92  4862.0 1740.75  4912.3 1738.86  4942.5 1736.77  4972.6 1736.57
  4979.3 1735.07  4979.8 1734.57  4986.2 1735.07  4992.8 1735.47  4998.3 1737.09
  5006.9 1737.54  5013.0 1739.26  5023.1 1740.50  5067.0 1742.23  5094.2 1744.38
  5104.3 1746.00  5127.1 1747.24  5226.1 1747.75  5242.2 1749.72  5389.9 1753.91
#Mann=3,-1,0
  4712.4    0.05       0  4979.3    0.05       0  4986.2    0.05       0
Bank Sta=4979.3,4986.2
Exp/Cntr=0.3,0.1