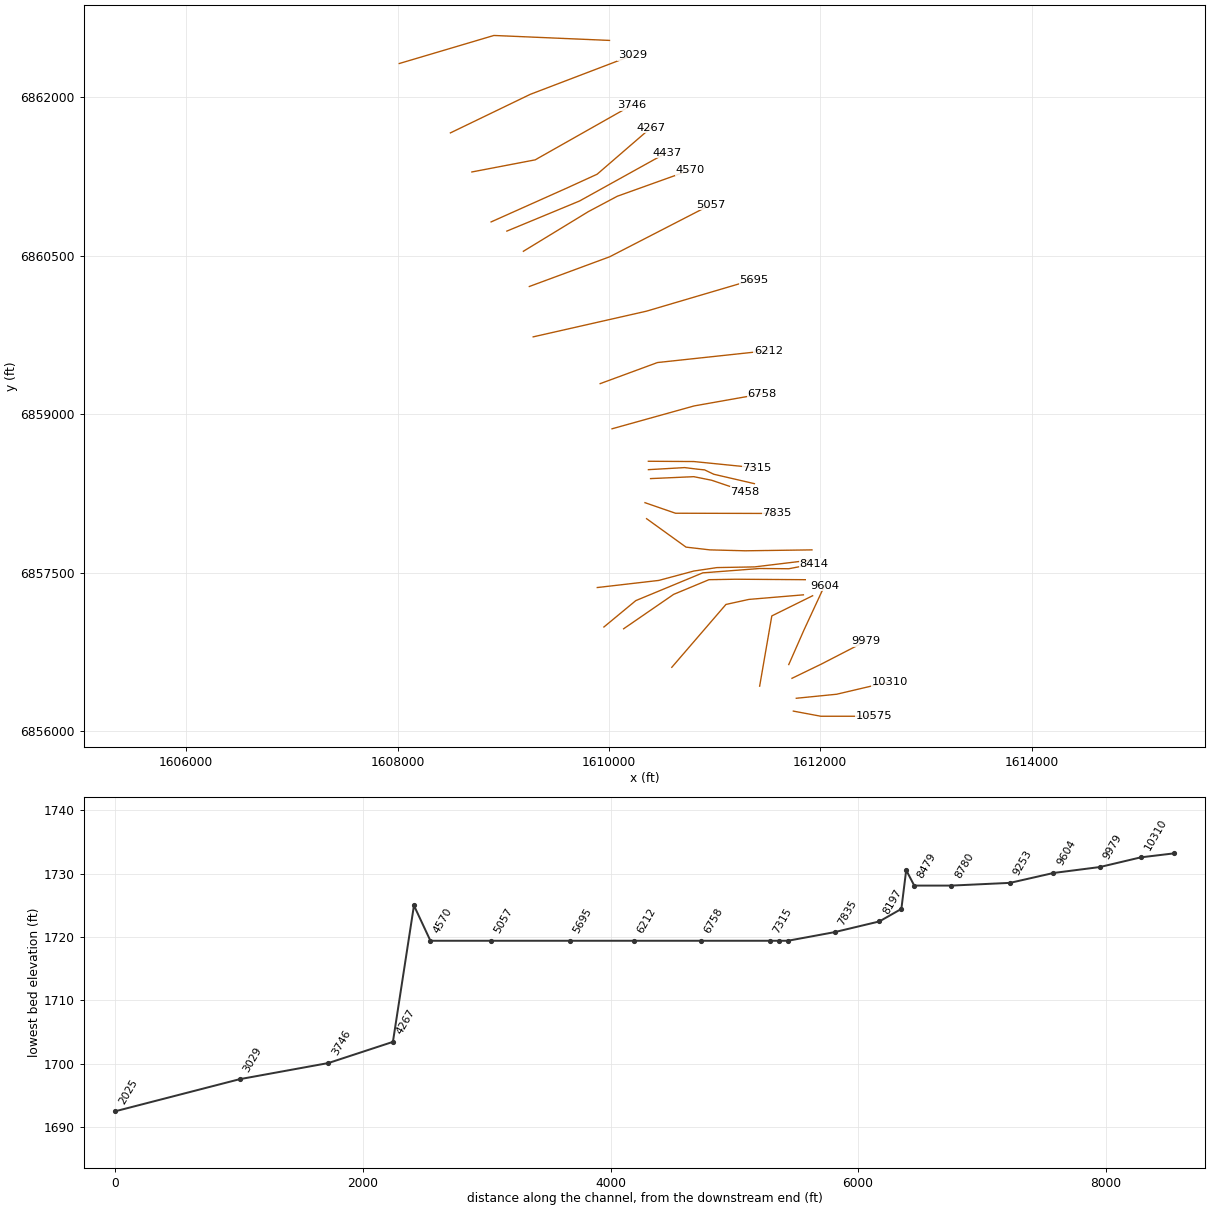
HEC-RAS study Elm 02 34.prj: Elm 02 34 Base Level Engineering

--- Elm 02 34.g01 (geometry) --- (continued)

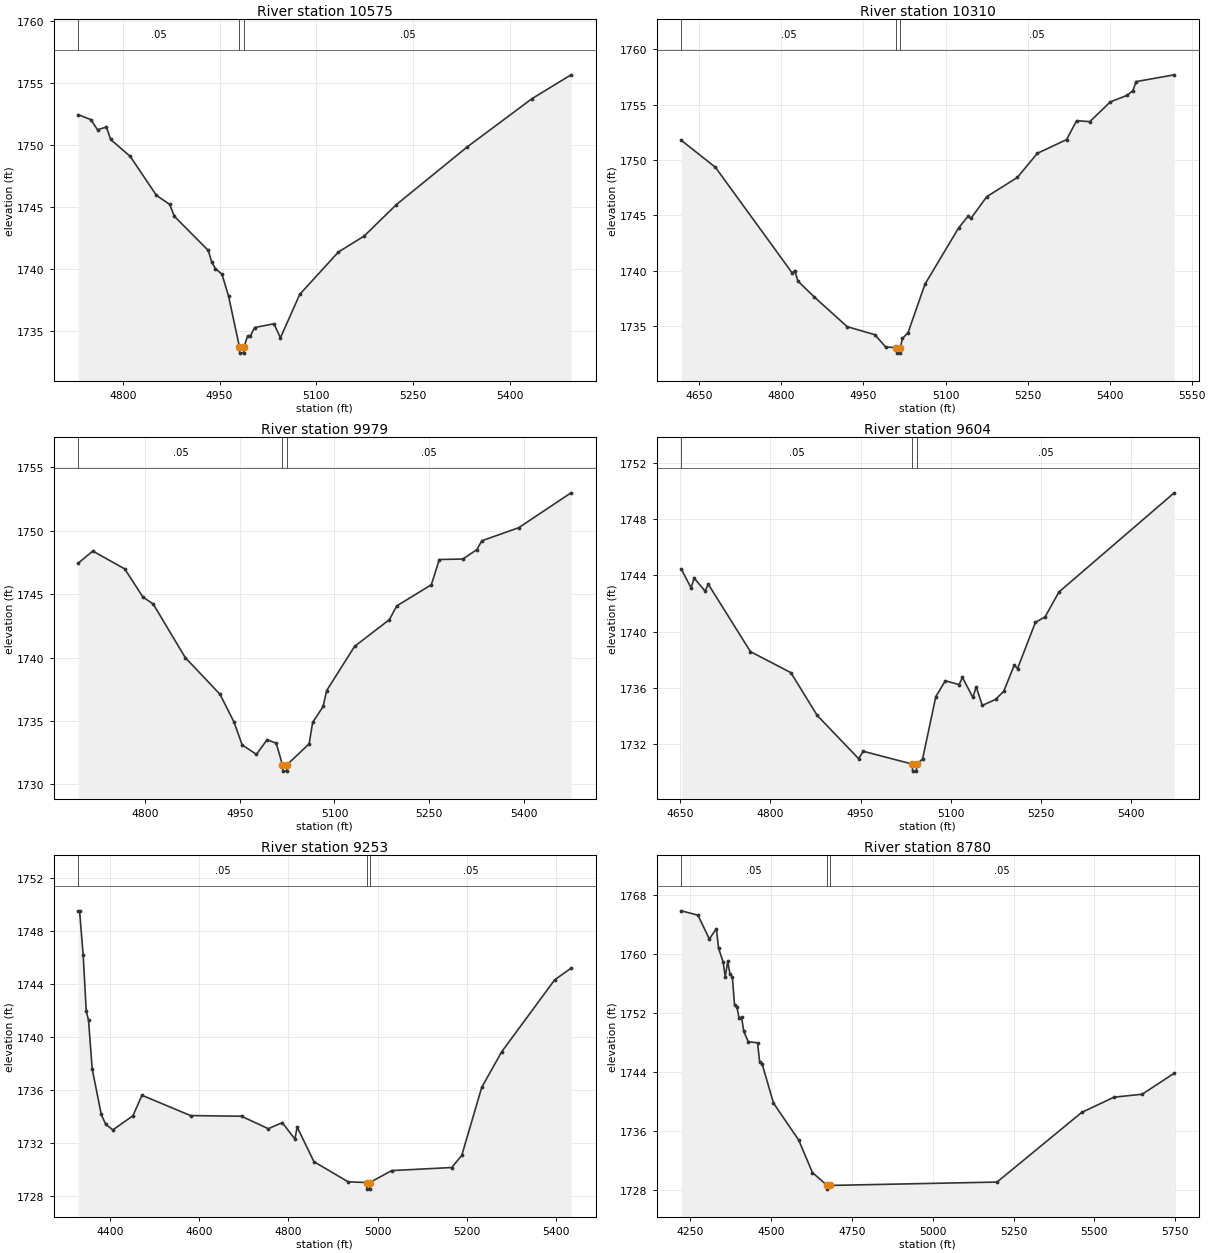
Type RM Length L Ch R = 1,10575,265,265,265
BEGIN DESCRIPTION:
Elm 02 34 10575.47
END DESCRIPTION:
XS GIS Cut Line= 3
      1611745.55      6856190.83      1612005.92      6856142.22
      1612505.95      6856142.22
#Sta/Elev= 30
  4730.5 1752.45  4750.3 1752.05  4760.5 1751.23  4774.4 1751.46  4780.8 1750.45
  4811.3 1749.08  4852.0 1745.93  4872.4 1745.21  4879.8 1744.24  4932.5 1741.48
  4937.6 1740.56  4943.6 1740.01  4953.7 1739.56  4963.9 1737.79  4980.8 1733.69
  4981.3 1733.19  4987.2 1733.19  4987.7 1733.69  4993.3 1734.55  4997.4 1734.55
  5004.4 1735.26  5034.4 1735.56  5044.4 1734.43  5074.4 1737.94  5134.4 1741.36
  5174.4 1742.65  5224.4 1745.19  5334.4 1749.85  5434.4 1753.73  5495.4 1755.67
#Mann=3,-1,0
  4730.5    0.05       0  4980.8    0.05       0  4987.7    0.05       0
Bank Sta=4980.8,4987.7
Exp/Cntr=0.3,0.1

Type RM Length L Ch R = 1,10310,331,331,331
BEGIN DESCRIPTION:
Elm 02 34 10309.93
END DESCRIPTION:
XS GIS Cut Line= 3
      1611773.25      6856312.36      1612155.23      6856350.56
      1612658.68      6856468.61
#Sta/Elev= 30
  4617.1 1751.78  4679.2 1749.36  4819.7 1739.81  4824.7 1740.03  4829.9 1739.09
  4860.1 1737.64  4920.2 1734.96  4970.6 1734.24  4990.7 1733.12  5010.4 1733.07
  5010.9 1732.57  5016.9 1732.57  5017.4 1733.07  5021.3 1733.90  5031.6 1734.43
  5062.4 1738.79  5124.0 1743.88  5141.3 1744.93  5146.4 1744.73  5175.4 1746.70
  5231.3 1748.43  5267.8 1750.61  5321.3 1751.85  5339.7 1753.56  5363.8 1753.47
  5401.1 1755.25  5432.1 1755.85  5442.4 1756.27  5448.6 1757.09  5518.1 1757.70
#Mann=3,-1,0
  4617.1    0.05       0  5010.4    0.05       0  5017.4    0.05       0
Bank Sta=5010.4,5017.4
Exp/Cntr=0.3,0.1

Type RM Length L Ch R = 1,9979,375,375,375
BEGIN DESCRIPTION:
Elm 02 34 9978.58
END DESCRIPTION:
XS GIS Cut Line= 3
      1611732.60      6856501.29      1612010.34      6856635.82
      1612430.68      6856852.49
#Sta/Elev= 30
  4693.6 1747.44  4716.7 1748.40  4767.4 1746.99  4796.3 1744.77  4812.6 1744.22
  4863.3 1740.00  4918.5 1737.10  4940.7 1734.91  4953.6 1733.11  4976.2 1732.36
  4993.2 1733.52  5007.6 1733.24  5017.5 1731.54  5018.0 1731.04  5024.1 1731.04
  5024.6 1731.54  5059.8 1733.19  5065.4 1734.88  5082.0 1736.14  5087.6 1737.39
  5131.9 1740.88  5187.1 1742.99  5198.7 1744.07  5253.6 1745.74  5266.2 1747.73
  5303.6 1747.77  5325.8 1748.51  5333.7 1749.21  5392.2 1750.24  5475.1 1752.99
#Mann=3,-1,0
  4693.6    0.05       0  5017.5    0.05       0  5024.6    0.05       0
Bank Sta=5017.5,5024.6
Exp/Cntr=0.3,0.1

Type RM Length L Ch R = 1,9604,351,351,351
BEGIN DESCRIPTION:
Elm 02 34 9604.37
END DESCRIPTION:
XS GIS Cut Line= 3
      1611702.19      6856631.51      1611845.41      6856957.00
      1612040.38      6857377.27
#Sta/Elev= 30
  4652.3 1744.43  4668.3 1743.12  4673.7 1743.79  4691.6 1742.88  4697.1 1743.36
  4767.1 1738.58  4834.2 1737.09  4877.9 1734.06  4946.9 1730.98  4954.4 1731.51
  5036.0 1730.60  5036.5 1730.10  5042.7 1730.10  5043.2 1730.60  5053.1 1730.96
  5075.1 1735.39  5090.9 1736.51  5113.8 1736.24  5119.3 1736.75  5136.7 1735.33
  5142.2 1736.09  5152.3 1734.76  5174.4 1735.19  5188.0 1735.77  5205.4 1737.62
  5210.9 1737.38  5240.5 1740.65  5256.7 1741.05  5279.6 1742.81  5471.2 1749.85
#Mann=3,-1,0
  4652.3    0.05       0  5036.0    0.05       0  5043.2    0.05       0
Bank Sta=5036,5043.2
Exp/Cntr=0.3,0.1

Type RM Length L Ch R = 1,9253,473,473,473
BEGIN DESCRIPTION:
Elm 02 34 9254.33
END DESCRIPTION:
XS GIS Cut Line= 3
      1611426.59      6856426.98      1611541.59      6857091.55
      1611927.91      6857282.54
#Sta/Elev= 30
  4328.4 1749.54  4331.5 1749.54  4339.6 1746.20  4346.5 1741.98  4351.6 1741.28
  4359.9 1737.59  4380.2 1734.18  4390.3 1733.42  4406.3 1733.01  4451.2 1734.08
  4471.5 1735.62  4580.5 1734.09  4694.8 1734.04  4754.8 1733.10  4786.1 1733.56
  4814.5 1732.32  4819.6 1733.22  4857.2 1730.61  4934.1 1729.09  4975.3 1729.04
  4975.8 1728.54  4982.1 1728.54  4982.6 1729.04  5031.6 1729.94  5166.2 1730.17
  5188.7 1731.08  5233.5 1736.22  5278.4 1738.91  5397.1 1744.33  5433.8 1745.21
#Mann=3,-1,0
  4328.4    0.05       0  4975.3    0.03       0  4982.6    0.05       0
Bank Sta=4975.3,4982.6
Exp/Cntr=0.3,0.1

Type RM Length L Ch R = 1,8780,301,301,301
BEGIN DESCRIPTION:
Elm 02 34 8779.55
END DESCRIPTION:
XS GIS Cut Line= 4
      1610595.38      6856605.41      1611107.56      6857200.06
      1611324.58      6857247.80      1611840.53      6857291.16
#Sta/Elev= 30
  4222.0 1765.91  4273.3 1765.32  4308.5 1762.09  4330.4 1763.49  4337.0 1760.84
  4351.2 1758.98  4357.8 1756.97  4365.5 1759.03  4372.1 1757.38  4379.8 1756.91
  4386.4 1753.18  4394.0 1752.84  4400.6 1751.33  4408.3 1751.48  4414.9 1749.54
  4429.1 1748.14  4457.7 1747.98  4464.3 1745.38  4471.9 1745.11  4507.0 1739.80
  4584.9 1734.78  4627.7 1730.35  4673.3 1728.61  4673.8 1728.11  4680.9 1728.61
  5198.7 1729.07  5460.3 1738.52  5560.6 1740.60  5647.6 1741.00  5746.8 1743.85
#Mann=3,-1,0
  4222.0    0.05       0  4673.3    0.03       0  4680.9    0.05       0
Bank Sta=4673.3,4680.9
Exp/Cntr=0.3,0.1

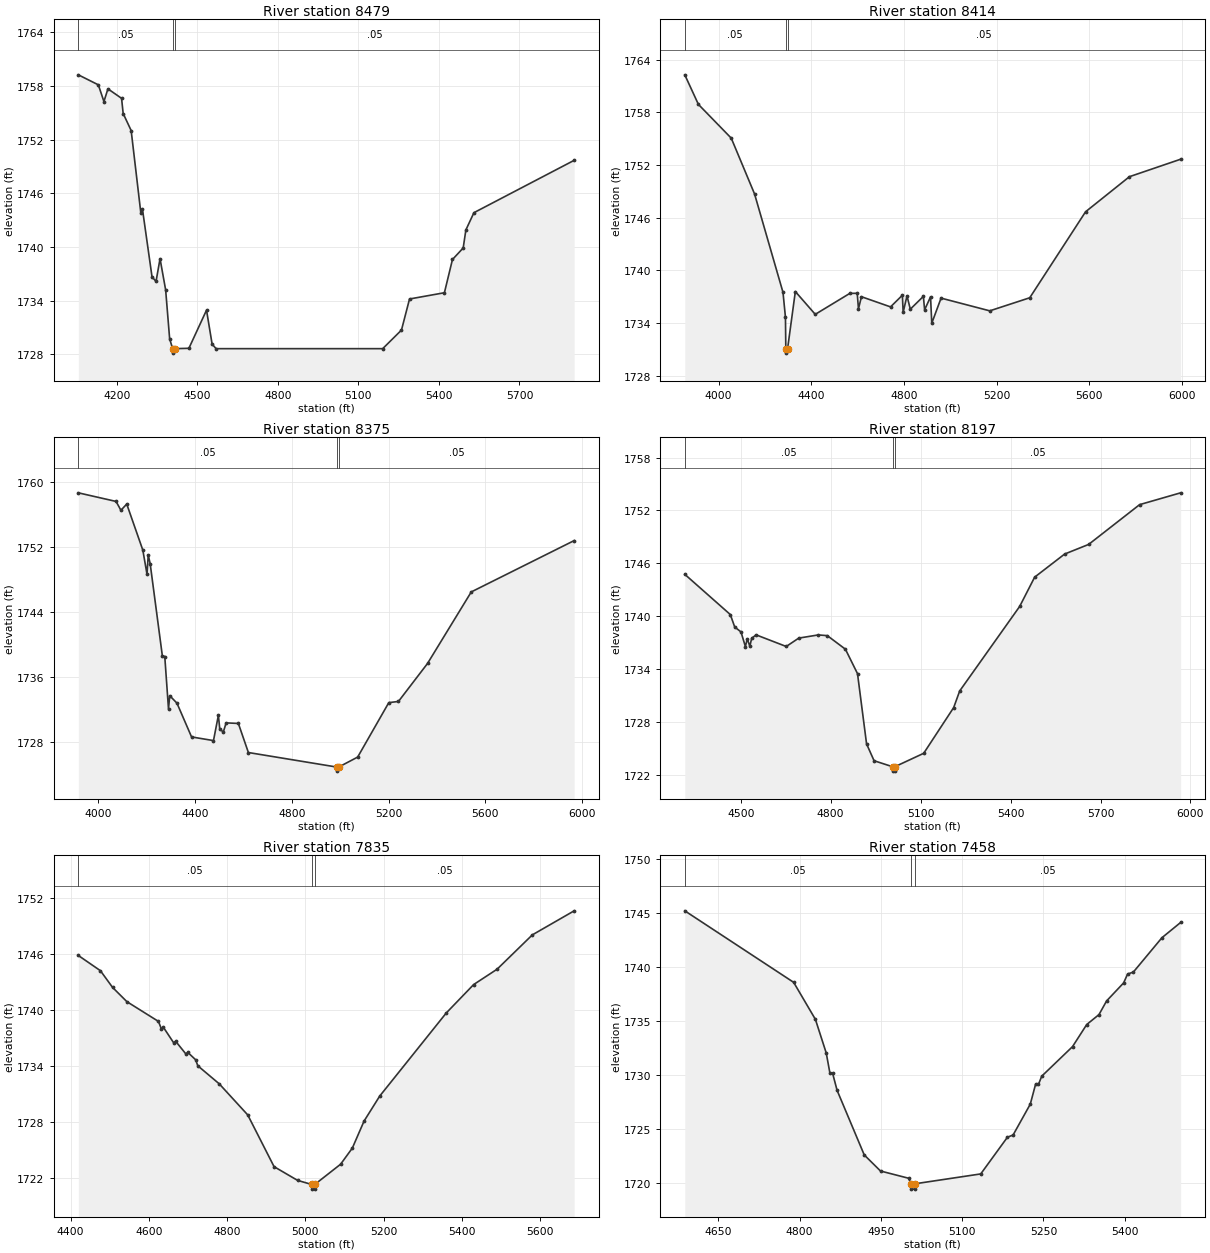
Type RM Length L Ch R = 1,8479,65,65,65
BEGIN DESCRIPTION:
Elm 02 34 8478.94
END DESCRIPTION:
XS GIS Cut Line= 5
      1610139.70      6856970.04      1610612.77      6857295.55
      1610946.97      6857434.44      1611198.71      6857438.78
      1611858.47      6857434.43
#Sta/Elev= 30
  4056.2 1759.26  4130.7 1758.14  4151.6 1756.27  4166.5 1757.69  4217.3 1756.63
  4223.3 1754.93  4253.1 1753.02  4289.0 1743.83  4295.0 1744.26  4330.9 1736.63
  4345.8 1736.14  4360.7 1738.68  4381.6 1735.18  4396.5 1729.71  4407.6 1728.61
  4408.1 1728.11  4415.2 1728.61  4468.2 1728.65  4533.9 1732.92  4554.8 1729.11
  4569.7 1728.61  5190.4 1728.61  5260.4 1730.69  5290.4 1734.17  5420.4 1734.87
  5450.4 1738.59  5490.4 1739.88  5500.4 1741.90  5530.4 1743.83  5903.9 1749.69
#Mann=3,-1,0
  4056.2    0.05       0  4407.6    0.03       0  4415.2    0.05       0
Bank Sta=4407.6,4415.2
Exp/Cntr=0.3,0.1

Type RM Length L Ch R = 1,8414,39,39,39
BEGIN DESCRIPTION:
Mapping XS fc50594d
END DESCRIPTION:
XS GIS Cut Line= 6
      1609953.10      6856986.92      1610254.72      6857236.46
      1610888.40      6857499.05      1611426.60      6857540.28
      1611702.20      6857538.11      1611940.93      6857583.68
#Sta/Elev= 30
  3854.5 1762.27  3913.2 1758.90  4055.0 1755.05  4155.4 1748.70  4278.2 1737.48
  4288.8 1734.64  4290.4 1731.05  4290.9 1730.55  4298.0 1731.05  4331.5 1737.57
  4417.4 1734.97  4566.6 1737.36  4598.5 1737.37  4603.9 1735.60  4616.7 1736.98
  4742.3 1735.82  4793.4 1737.15  4796.7 1735.21  4813.3 1737.07  4827.6 1735.56
  4884.0 1737.02  4889.3 1735.48  4914.9 1736.97  4920.2 1733.96  4960.3 1736.82
  5170.4 1735.37  5343.0 1736.86  5583.8 1746.66  5773.1 1750.66  5994.0 1752.65
#Mann=3,-1,0
  3854.5    0.05       0  4290.4    0.05       0  4298.0    0.05       0
Bank Sta=4290.4,4298
Exp/Cntr=0.3,0.1

Type RM Length L Ch R = 1,8375,178,178,178
BEGIN DESCRIPTION:
Mapping XS 95bf2794
END DESCRIPTION:
XS GIS Cut Line= 6
      1609890.17      6857360.16      1610471.74      6857427.43
      1610803.77      6857516.41      1611022.95      6857548.96
      1611378.85      6857555.47      1611917.09      6857620.58
#Sta/Elev= 30
  3918.1 1758.69  4074.0 1757.63  4094.1 1756.54  4118.1 1757.31  4184.7 1751.63
  4201.9 1748.66  4206.9 1751.04  4214.9 1749.98  4265.2 1738.64  4275.3 1738.54
  4290.7 1732.08  4295.7 1733.72  4325.6 1732.80  4386.0 1728.64  4476.6 1728.19
  4496.8 1731.30  4502.7 1729.58  4517.3 1729.26  4528.9 1730.37  4579.4 1730.30
  4620.8 1726.72  4986.3 1724.93  4986.8 1724.43  4993.9 1724.93  5072.4 1726.16
  5201.0 1732.86  5241.0 1733.01  5361.0 1737.68  5541.8 1746.49  5967.0 1752.81
#Mann=3,-1,0
  3918.1    0.05       0  4986.3    0.05       0  4993.9    0.05       0
Bank Sta=4986.3,4993.9
Exp/Cntr=0.3,0.1

Type RM Length L Ch R = 1,8197,362,362,362
BEGIN DESCRIPTION:
Elm 02 34 8196.85
END DESCRIPTION:
XS GIS Cut Line= 5
      1610356.70      6858011.69      1610729.96      6857742.59
      1610955.65      6857716.55      1611289.85      6857707.87
      1611921.74      6857716.53
#Sta/Elev= 30
  4313.6 1744.76  4465.4 1740.20  4480.1 1738.79  4501.0 1738.23  4515.7 1736.57
  4521.9 1737.45  4530.5 1736.61  4536.6 1737.50  4551.3 1737.90  4651.9 1736.58
  4693.7 1737.53  4758.7 1737.89  4788.9 1737.81  4849.3 1736.27  4889.6 1733.50
  4919.8 1725.54  4944.8 1723.63  5006.4 1722.95  5006.9 1722.45  5013.7 1722.45
  5014.2 1722.95  5110.3 1724.47  5210.4 1729.66  5230.4 1731.54  5430.4 1741.12
  5480.4 1744.44  5580.4 1747.06  5660.4 1748.15  5830.4 1752.66  5967.2 1754.00
#Mann=3,-1,0
  4313.6    0.05       0  5006.4    0.03       0  5014.2    0.05       0
Bank Sta=5006.4,5014.2
Exp/Cntr=0.3,0.1

Type RM Length L Ch R = 1,7835,377,377,377
BEGIN DESCRIPTION:
Mapping XS bbe6bead
END DESCRIPTION:
XS GIS Cut Line= 3
      1610341.54      6858163.10      1610630.16      6858063.28
      1611591.87      6858061.12
#Sta/Elev= 30
  4419.9 1745.82  4476.3 1744.19  4507.5 1742.39  4543.9 1740.87  4624.6 1738.75
  4632.1 1737.95  4637.4 1738.11  4663.3 1736.47  4668.6 1736.62  4694.5 1735.27
  4699.8 1735.42  4719.8 1734.63  4725.2 1733.99  4780.1 1732.05  4852.8 1728.72
  4920.1 1723.17  4980.1 1721.70  5016.2 1721.26  5016.7 1720.76  5023.6 1720.76
  5024.1 1721.26  5090.1 1723.43  5120.1 1725.16  5150.1 1728.06  5190.1 1730.74
  5360.1 1739.65  5430.1 1742.70  5490.1 1744.35  5580.1 1748.03  5687.0 1750.61
#Mann=3,-1,0
  4419.9    0.05       0  5016.2    0.03       0  5024.1    0.05       0
Bank Sta=5016.2,5024.1
Exp/Cntr=0.3,0.1

Type RM Length L Ch R = 1,7458,75,75,75
BEGIN DESCRIPTION:
Elm 02 34 7458.16
END DESCRIPTION:
XS GIS Cut Line= 4
      1610394.37      6858391.00      1610803.25      6858409.23
      1610972.52      6858375.38      1611287.62      6858268.61
#Sta/Elev= 30
  4588.4 1745.20  4789.2 1738.57  4829.3 1735.14  4849.3 1732.02  4856.0 1730.18
  4861.0 1730.15  4869.3 1728.56  4919.4 1722.57  4949.4 1721.08  5001.1 1720.41
  5005.7 1719.90  5006.2 1719.40  5013.1 1719.40  5013.6 1719.90  5134.3 1720.81
  5183.5 1724.21  5194.0 1724.42  5225.7 1727.28  5235.5 1729.13  5240.8 1729.11
  5246.8 1729.87  5303.6 1732.61  5329.8 1734.66  5352.4 1735.58  5366.5 1736.85
  5397.9 1738.52  5405.2 1739.34  5415.8 1739.52  5468.6 1742.71  5503.0 1744.12
#Mann=3,-1,0
  4588.4    0.05       0  5005.7    0.03       0  5013.6    0.05       0
Bank Sta=5005.7,5013.6
Exp/Cntr=0.3,0.1

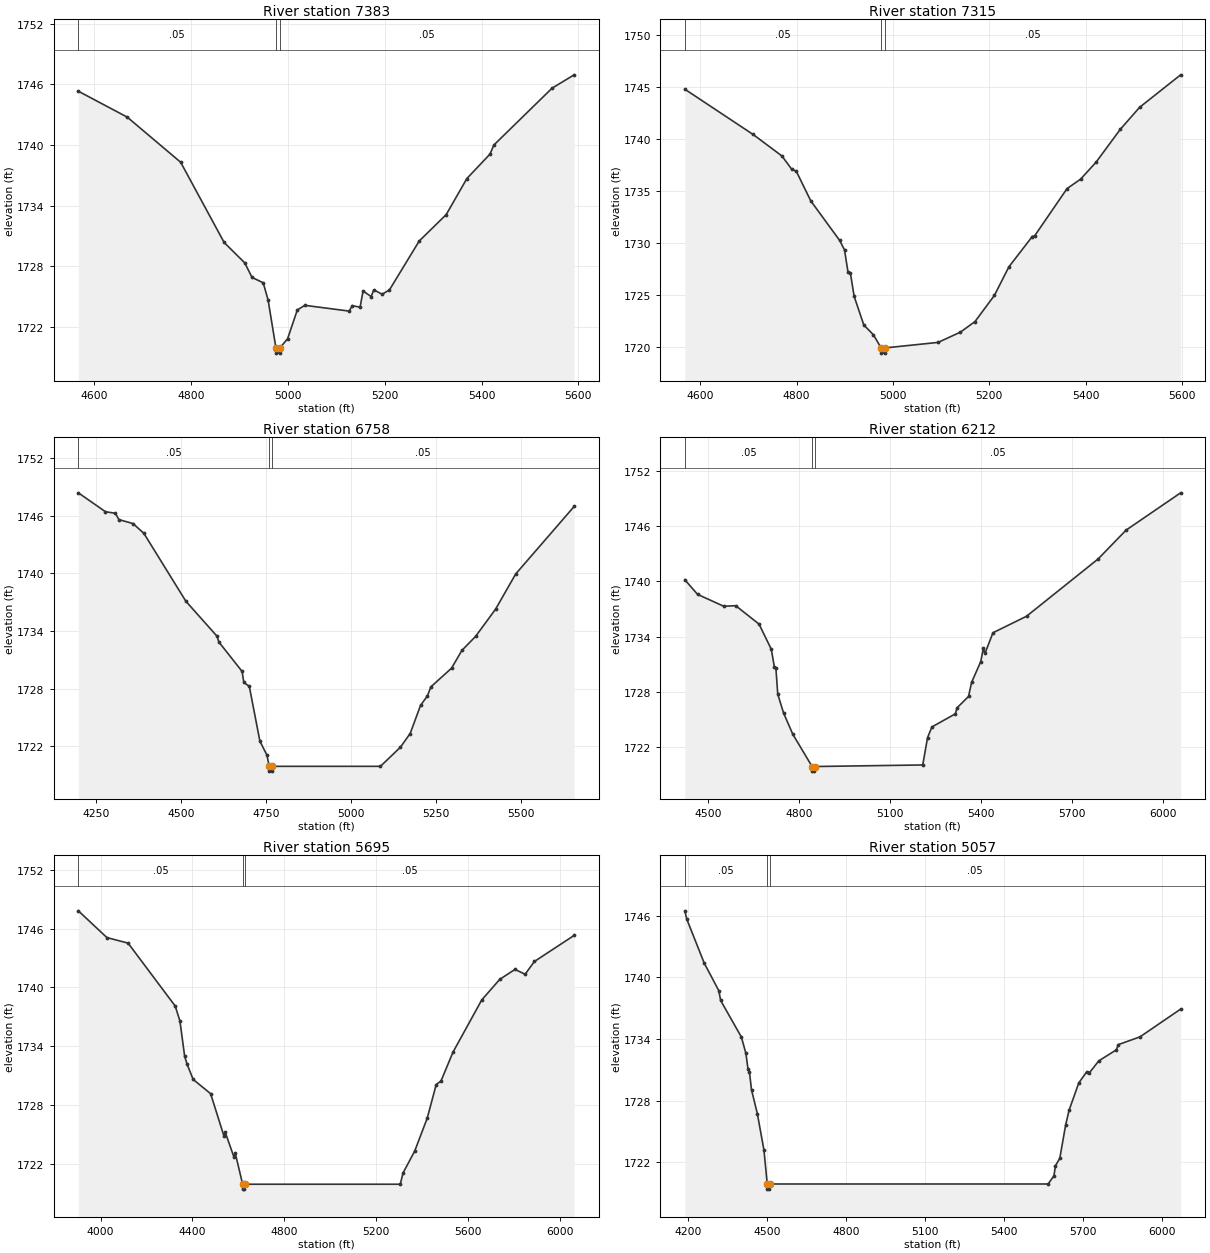
Type RM Length L Ch R = 1,7383,68,68,68
BEGIN DESCRIPTION:
Mapping XS 5632e90c
END DESCRIPTION:
XS GIS Cut Line= 6
      1610374.04      6858475.61      1610716.96      6858495.14
      1610840.66      6858479.95      1610905.76      6858473.44
      1610992.57      6858432.21      1611376.67      6858343.23
#Sta/Elev= 30
  4567.3 1745.32  4668.4 1742.75  4778.6 1738.29  4868.4 1730.35  4910.8 1728.34
  4926.1 1726.89  4949.1 1726.36  4959.2 1724.65  4975.4 1719.90  4975.9 1719.40
  4982.8 1719.40  4983.3 1719.90  4999.5 1720.83  5019.6 1723.68  5035.1 1724.13
  5126.4 1723.56  5133.2 1724.10  5149.1 1723.94  5155.3 1725.55  5171.9 1725.00
  5177.5 1725.66  5194.6 1725.23  5209.7 1725.65  5271.3 1730.50  5327.0 1733.11
  5369.7 1736.68  5417.5 1739.10  5425.3 1739.99  5545.6 1745.62  5591.2 1746.94
#Mann=3,-1,0
  4567.3    0.05       0  4975.4    0.03       0  4983.3    0.05       0
Bank Sta=4975.4,4983.3
Exp/Cntr=0.3,0.1

Type RM Length L Ch R = 1,7315,557,557,557
BEGIN DESCRIPTION:
Elm 02 34 7314.7
END DESCRIPTION:
XS GIS Cut Line= 3
      1610373.54      6858555.07      1610803.25      6858552.46
      1611399.63      6858492.56
#Sta/Elev= 30
  4568.0 1744.75  4709.5 1740.41  4769.5 1738.34  4789.5 1737.09  4799.5 1736.86
  4829.5 1734.02  4889.5 1730.22  4899.5 1729.31  4906.7 1727.20  4911.7 1727.09
  4919.5 1724.85  4939.5 1722.11  4959.5 1721.16  4975.5 1719.90  4976.0 1719.40
  4982.9 1719.40  4983.4 1719.90  5093.7 1720.43  5140.2 1721.42  5170.3 1722.43
  5210.5 1724.94  5240.7 1727.69  5289.2 1730.60  5294.2 1730.67  5361.3 1735.20
  5389.5 1736.11  5421.6 1737.74  5471.8 1740.89  5512.0 1743.01  5597.1 1746.13
#Mann=3,-1,0
  4568.0    0.05       0  4975.5    0.05       0  4983.4    0.05       0
Bank Sta=4975.5,4983.4
Exp/Cntr=0.3,0.1

Type RM Length L Ch R = 1,6758,546,546,546
BEGIN DESCRIPTION:
Elm 02 34 6757.79
END DESCRIPTION:
XS GIS Cut Line= 3
      1610029.86      6858862.37      1610805.86      6859078.50
      1611450.56      6859192.89
#Sta/Elev= 30
  4197.4 1748.40  4277.4 1746.43  4306.5 1746.27  4316.9 1745.61  4358.4 1745.20
  4390.4 1744.18  4514.2 1737.10  4606.1 1733.45  4611.2 1732.86  4679.7 1729.79
  4684.8 1728.64  4701.0 1728.23  4732.1 1722.53  4752.9 1721.06  4759.6 1719.90
  4760.1 1719.40  4767.2 1719.40  4767.7 1719.90  5087.2 1719.90  5146.2 1721.90
  5174.7 1723.32  5205.3 1726.25  5225.5 1727.24  5235.7 1728.18  5296.6 1730.13
  5327.1 1731.98  5367.4 1733.44  5426.5 1736.29  5485.6 1739.95  5657.7 1746.98
#Mann=3,-1,0
  4197.4    0.05       0  4759.6    0.03       0  4767.7    0.05       0
Bank Sta=4759.6,4767.7
Exp/Cntr=0.3,0.1

Type RM Length L Ch R = 1,6212,517,517,517
BEGIN DESCRIPTION:
Elm 02 34 6212.19
END DESCRIPTION:
XS GIS Cut Line= 3
      1609917.41      6859289.57      1610459.91      6859489.21
      1611510.10      6859602.04
#Sta/Elev= 30
  4422.6 1740.19  4464.7 1738.60  4550.8 1737.31  4590.5 1737.37  4667.3 1735.37
  4707.7 1732.64  4717.6 1730.76  4722.9 1730.57  4729.0 1727.76  4748.0 1725.73
  4778.5 1723.41  4842.2 1719.90  4842.7 1719.40  4849.9 1719.40  4850.4 1719.90
  5206.9 1720.07  5222.7 1723.03  5237.1 1724.20  5314.8 1725.63  5319.8 1726.27
  5357.8 1727.51  5367.9 1729.04  5398.0 1731.29  5406.8 1732.74  5411.9 1732.18
  5438.3 1734.43  5548.9 1736.22  5785.1 1742.45  5877.2 1745.58  6056.9 1749.63
#Mann=3,-1,0
  4422.6    0.05       0  4842.2    0.03       0  4850.4    0.05       0
Bank Sta=4842.2,4850.4
Exp/Cntr=0.3,0.1

Type RM Length L Ch R = 1,5695,638,638,638
BEGIN DESCRIPTION:
Elm 02 34 5694.96
END DESCRIPTION:
XS GIS Cut Line= 3
      1609283.73      6859732.27      1610355.74      6859975.32
      1611370.72      6860274.61
#Sta/Elev= 30
  3903.4 1747.82  4027.7 1745.09  4120.0 1744.52  4325.1 1738.09  4345.6 1736.55
  4366.1 1732.96  4376.4 1732.17  4403.1 1730.60  4478.9 1729.15  4537.6 1724.78
  4542.7 1725.20  4580.7 1722.66  4585.8 1723.12  4618.3 1719.90  4618.8 1719.40
  4626.1 1719.40  4626.6 1719.90  5304.2 1719.90  5316.2 1721.05  5366.7 1723.27
  5421.4 1726.64  5460.6 1730.08  5481.4 1730.44  5533.6 1733.39  5658.7 1738.72
  5736.9 1740.82  5803.5 1741.84  5847.3 1741.34  5888.0 1742.65  6060.8 1745.31
#Mann=3,-1,0
  3903.4    0.05       0  4618.3    0.03       0  4626.6    0.05       0
Bank Sta=4618.3,4626.6
Exp/Cntr=0.3,0.1

Type RM Length L Ch R = 1,5057,487,487,487
BEGIN DESCRIPTION:
Elm 02 34 5056.56
END DESCRIPTION:
XS GIS Cut Line= 3
      1609247.21      6860208.82      1610007.65      6860490.08
      1610961.68      6860981.39
#Sta/Elev= 30
  4186.6 1746.47  4194.1 1745.66  4260.3 1741.39  4315.7 1738.71  4322.9 1737.75
  4401.6 1734.19  4418.8 1732.60  4426.7 1731.08  4432.0 1730.84  4440.1 1729.06
  4462.4 1726.72  4487.5 1723.17  4499.8 1719.90  4500.3 1719.40  4508.0 1719.40
  4508.5 1719.90  5567.0 1719.90  5589.2 1720.69  5594.8 1721.67  5611.4 1722.40
  5633.6 1725.63  5646.8 1727.08  5683.5 1729.73  5714.3 1730.83  5722.2 1730.66
  5759.3 1731.87  5826.8 1732.96  5833.1 1733.45  5916.1 1734.21  6070.5 1736.91
#Mann=3,-1,0
  4186.6    0.05       0  4499.8    0.03       0  4508.5    0.05       0
Bank Sta=4499.8,4508.5
Exp/Cntr=0.3,0.1

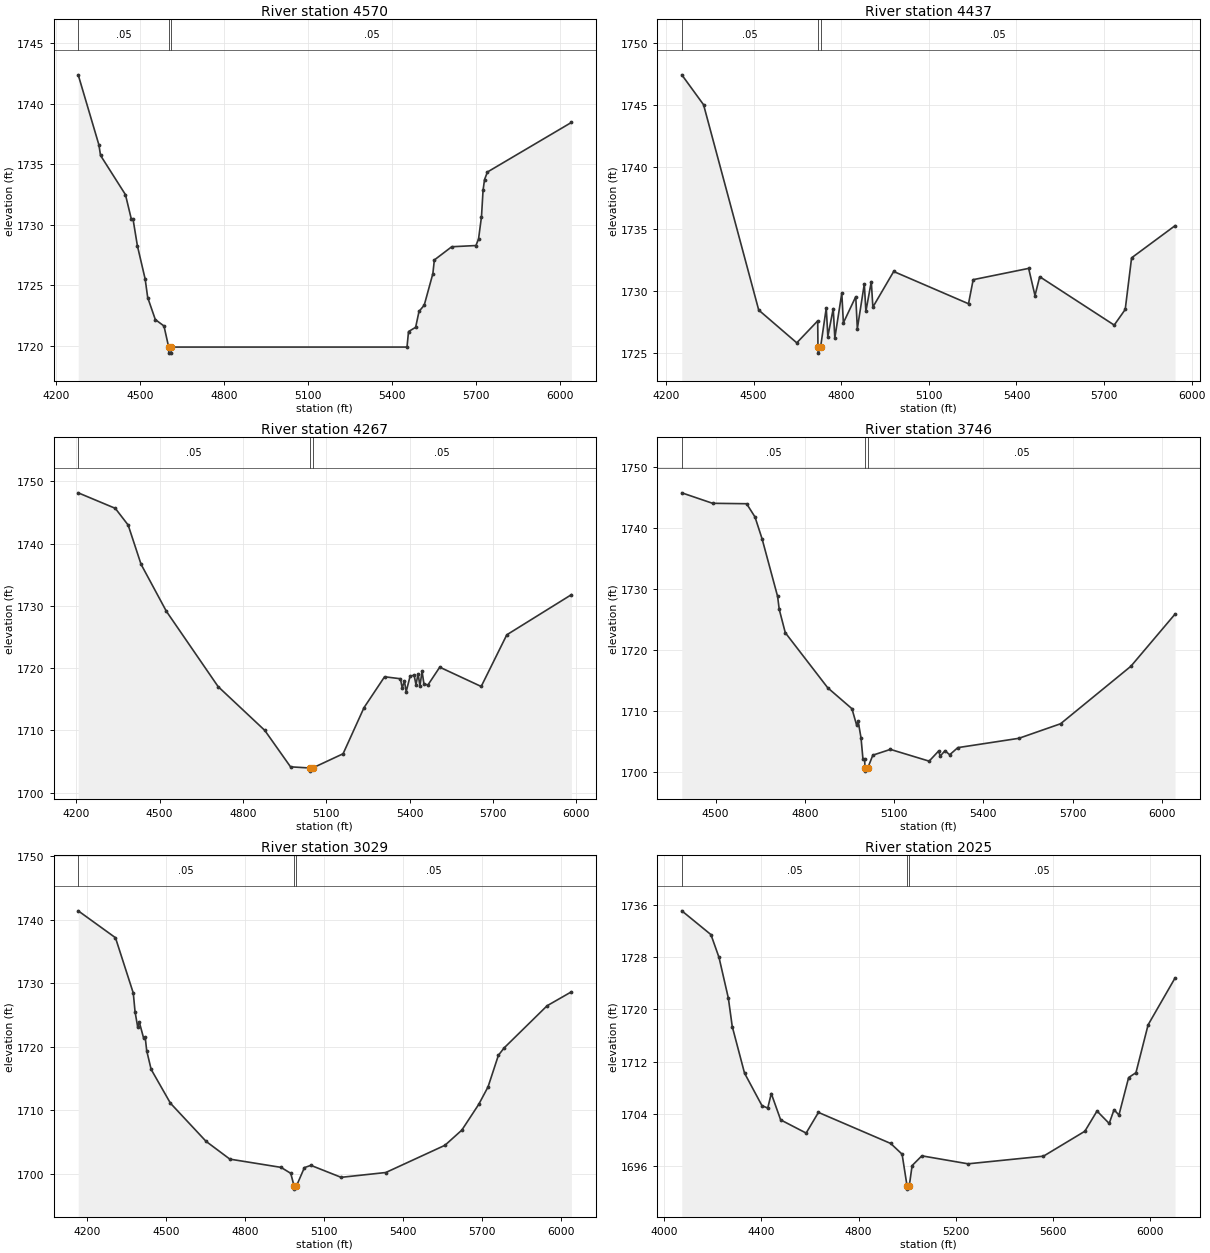
Type RM Length L Ch R = 1,4570,133,133,133
BEGIN DESCRIPTION:
Elm 02 34 4570.41
END DESCRIPTION:
XS GIS Cut Line= 4
      1609190.93      6860542.10      1609805.48      6860917.07
      1610079.79      6861062.91      1610767.25      6861309.42
#Sta/Elev= 30
  4280.3 1742.37  4354.2 1736.59  4360.0 1735.72  4449.0 1732.48  4470.3 1730.43
  4476.2 1730.44  4491.6 1728.26  4519.4 1725.51  4528.4 1723.99  4555.6 1722.17
  4586.5 1721.64  4603.3 1719.90  4603.8 1719.40  4611.8 1719.40  4612.3 1719.90
  5454.2 1719.90  5459.6 1721.18  5485.0 1721.53  5497.0 1722.84  5515.7 1723.36
  5546.5 1725.96  5551.8 1727.09  5613.9 1728.18  5700.2 1728.28  5709.5 1728.81
  5720.1 1730.66  5725.7 1732.84  5731.0 1733.73  5741.4 1734.35  6041.2 1738.44
#Mann=3,-1,0
  4280.3    0.05       0  4603.3    0.03       0  4612.3    0.05       0
Bank Sta=4603.3,4612.3
Exp/Cntr=0.3,0.1

Type RM Length L Ch R = 1,4437,170,170,170
BEGIN DESCRIPTION:
Elm 02 34 4437.35
END DESCRIPTION:
XS GIS Cut Line= 3
      1609034.61      6860733.03      1609722.15      6861017.77
      1610548.50      6861476.08
#Sta/Elev= 30
  4254.0 1747.40  4328.5 1744.99  4517.4 1728.44  4647.7 1725.80  4719.4 1727.57
  4720.3 1725.47  4720.8 1724.97  4729.3 1725.47  4748.7 1728.61  4754.1 1726.31
  4772.6 1728.56  4778.0 1726.18  4801.9 1729.81  4807.3 1727.41  4849.7 1729.52
  4855.1 1726.94  4879.0 1730.55  4884.4 1728.34  4902.9 1730.73  4908.3 1728.68
  4979.6 1731.55  5235.8 1728.95  5251.8 1730.89  5441.8 1731.80  5463.5 1729.61
  5479.6 1731.13  5734.8 1727.23  5772.5 1728.49  5794.3 1732.65  5943.1 1735.24
#Mann=3,-1,0
  4254.0    0.05       0  4720.3    0.05       0  4729.3    0.05       0
Bank Sta=4720.3,4729.3
Exp/Cntr=0.3,0.1

Type RM Length L Ch R = 1,4267,521,521,521
BEGIN DESCRIPTION:
Elm 02 34 4266.7
END DESCRIPTION:
XS GIS Cut Line= 4
      1608885.34      6860819.85      1609607.56      6861142.77
      1609888.81      6861271.24      1610399.26      6861712.24
#Sta/Elev= 30
  4207.4 1748.15  4340.8 1745.66  4387.2 1742.97  4433.6 1736.67  4524.7 1729.12
  4710.9 1717.02  4878.7 1709.99  4971.5 1704.13  5041.7 1703.94  5042.2 1703.44
  5050.7 1703.94  5160.6 1706.23  5235.9 1713.64  5309.9 1718.60  5366.9 1718.28
  5373.5 1716.77  5381.1 1717.96  5387.7 1716.22  5402.0 1718.73  5416.3 1718.83
  5422.9 1717.33  5430.5 1719.08  5437.1 1717.13  5444.8 1719.47  5451.4 1717.50
  5465.6 1717.26  5508.4 1720.14  5657.6 1717.04  5749.7 1725.34  5982.3 1731.79
#Mann=3,-1,0
  4207.4    0.05       0  5041.7    0.05       0  5050.7    0.05       0
Bank Sta=5041.7,5050.7
Exp/Cntr=0.3,0.1

Type RM Length L Ch R = 1,3746,717,717,717
BEGIN DESCRIPTION:
Elm 02 34 3745.63
END DESCRIPTION:
XS GIS Cut Line= 3
      1608703.58      6861292.61      1609302.56      6861407.19
      1610213.98      6861922.80
#Sta/Elev= 30
  4386.8 1745.81  4490.1 1744.09  4604.5 1744.02  4632.6 1741.85  4656.5 1738.25
  4708.6 1728.80  4714.1 1726.67  4734.4 1722.84  4877.0 1713.79  4958.4 1710.35
  4974.0 1707.67  4979.1 1708.33  4988.9 1705.55  4995.3 1702.10  5000.9 1702.10
  5002.3 1700.60  5002.8 1700.10  5011.4 1700.60  5028.5 1702.72  5087.6 1703.67
  5217.7 1701.74  5249.3 1703.39  5255.1 1702.58  5271.0 1703.45  5286.7 1702.79
  5314.2 1703.96  5519.2 1705.49  5659.2 1707.88  5895.6 1717.33  6043.8 1725.89
#Mann=3,-1,0
  4386.8    0.05       0  5002.3    0.05       0  5011.4    0.05       0
Bank Sta=5002.3,5011.4
Exp/Cntr=0.3,0.1

Type RM Length L Ch R = 1,3029,1004,1004,1004
BEGIN DESCRIPTION:
Elm 02 34 3029.35
END DESCRIPTION:
XS GIS Cut Line= 3
      1608500.44      6861662.38      1609255.68      6862026.98
      1610224.45      6862396.78
#Sta/Elev= 30
  4165.2 1741.43  4306.9 1737.19  4374.7 1728.46  4381.3 1725.54  4391.7 1723.04
  4397.3 1723.93  4414.3 1721.30  4419.9 1721.54  4425.7 1719.37  4442.5 1716.44
  4515.9 1711.10  4651.5 1705.08  4741.9 1702.28  4936.5 1700.98  4973.5 1700.04
  4986.0 1698.05  4986.5 1697.55  4995.2 1698.05  5025.3 1700.94  5050.0 1701.30
  5165.0 1699.41  5334.9 1700.17  5559.7 1704.46  5623.9 1706.85  5688.2 1710.91
  5723.7 1713.67  5763.1 1718.65  5784.5 1719.80  5948.2 1726.46  6040.8 1728.66
#Mann=3,-1,0
  4165.2    0.05       0  4986.0    0.05       0  4995.2    0.05       0
Bank Sta=4986,4995.2
Exp/Cntr=0.3,0.1

Type RM Length L Ch R = 1,2025,405,405,405
BEGIN DESCRIPTION:
Elm 02 34 2024.76
END DESCRIPTION:
XS GIS Cut Line= 3
      1608016.06      6862318.64      1608911.93      6862584.28
      1610005.70      6862537.40
#Sta/Elev= 30
  4072.5 1735.04  4192.4 1731.40  4225.6 1727.91  4264.0 1721.69  4280.0 1717.35
  4330.5 1710.23  4402.2 1705.26  4426.0 1704.88  4440.6 1707.11  4479.1 1703.08
  4584.0 1701.06  4634.6 1704.22  4932.0 1699.47  4978.8 1697.83  4999.1 1692.99
  4999.6 1692.49  5008.3 1692.99  5020.0 1696.09  5060.0 1697.58  5250.2 1696.36
  5560.5 1697.53  5730.7 1701.34  5780.7 1704.43  5830.8 1702.53  5850.8 1704.64
  5870.8 1703.81  5910.8 1709.55  5940.9 1710.29  5990.9 1717.61  6101.7 1724.77
#Mann=3,-1,0
  4072.5    0.05       0  4999.1    0.03       0  5008.3    0.05       0
Bank Sta=4999.1,5008.3
Exp/Cntr=0.3,0.1