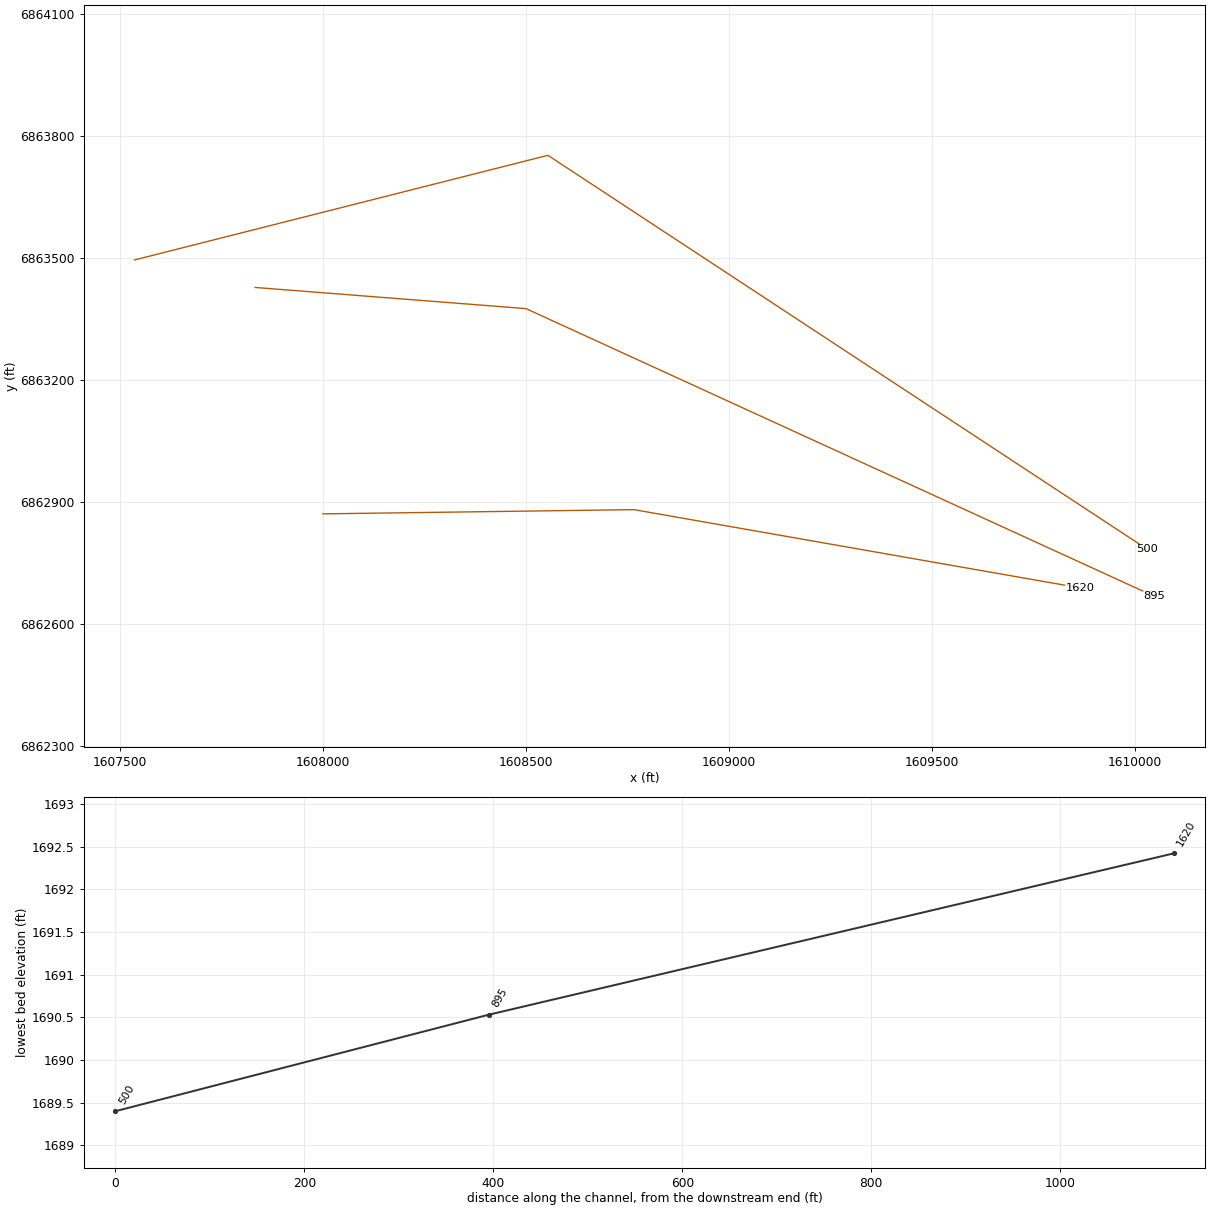
HEC-RAS study Elm 02 34.prj: Elm 02 34 Base Level Engineering

--- Elm 02 34.g01 (geometry) --- (continued)

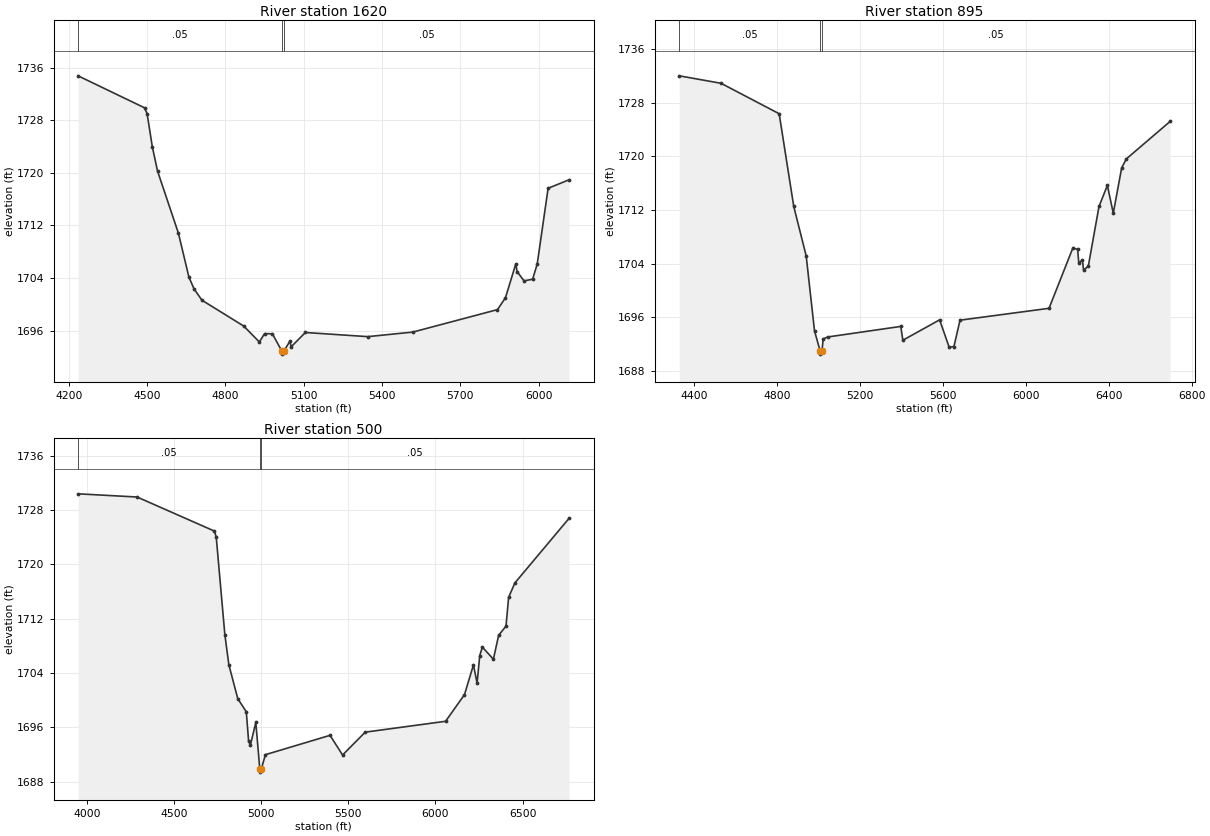
Type RM Length L Ch R = 1,1620,725,725,725
BEGIN DESCRIPTION:
Elm 02 34 1620.01
END DESCRIPTION:
XS GIS Cut Line= 3
      1608000.48      6862870.73      1608766.10      6862881.15
      1609865.04      6862688.44
#Sta/Elev= 30
  4235.2 1734.74  4489.7 1729.88  4499.7 1728.98  4519.7 1723.94  4539.7 1720.25
  4619.8 1710.79  4659.8 1704.14  4679.8 1702.32  4709.8 1700.62  4869.8 1696.69
  4929.8 1694.27  4949.8 1695.53  4979.8 1695.52  5015.5 1692.92  5016.0 1692.42
  5024.7 1692.92  5046.8 1694.39  5051.8 1693.54  5106.2 1695.71  5345.0 1695.08
  5517.6 1695.77  5842.4 1699.19  5872.9 1700.99  5912.5 1706.13  5917.6 1704.97
  5944.0 1703.56  5977.0 1703.81  5994.7 1706.13  6036.4 1717.64  6116.6 1718.93
#Mann=3,-1,0
  4235.2    0.05       0  5015.5    0.05       0  5024.7    0.05       0
Bank Sta=5015.5,5024.7
Exp/Cntr=0.3,0.1

Type RM Length L Ch R = 1,895,395,395,395
BEGIN DESCRIPTION:
Elm 02 34 895.09
END DESCRIPTION:
XS GIS Cut Line= 3
      1607833.82      6863428.03      1608500.47      6863375.94
      1610047.33      6862667.62
#Sta/Elev= 30
  4326.2 1732.01  4528.0 1730.90  4808.8 1726.36  4879.1 1712.55  4939.2 1705.17
  4979.4 1693.99  5006.2 1691.03  5006.7 1690.53  5015.6 1691.03  5021.2 1692.81
  5043.9 1693.09  5395.8 1694.66  5405.8 1692.60  5583.3 1695.64  5629.4 1691.56
  5652.4 1691.66  5681.8 1695.59  6111.5 1697.36  6226.6 1706.36  6249.6 1706.13
  6255.1 1704.10  6272.6 1704.57  6278.1 1703.05  6301.1 1703.64  6352.7 1712.54
  6393.1 1715.68  6421.6 1711.53  6462.1 1718.29  6484.7 1719.63  6696.2 1725.22
#Mann=3,-1,0
  4326.2    0.05       0  5006.2    0.05       0  5015.6    0.05       0
Bank Sta=5006.2,5015.6
Exp/Cntr=0.3,0.1

Type RM Length L Ch R = 1,500,0,0,0
BEGIN DESCRIPTION:
Elm 02 34 1911.981
END DESCRIPTION:
XS GIS Cut Line= 3
      1607536.97      6863495.74      1608554.48      6863753.26
      1610030.28      6862783.14
#Sta/Elev= 30
  3950.4 1730.40  4288.8 1729.93  4732.3 1724.91  4742.7 1724.02  4792.1 1709.67
  4814.9 1705.23  4866.4 1700.21  4915.1 1698.29  4928.3 1693.97  4938.6 1693.38
  4969.6 1696.72  4992.4 1689.90  4992.9 1689.40  5001.8 1689.90  5024.6 1691.97
  5395.3 1694.82  5467.3 1691.92  5597.1 1695.29  6058.0 1696.89  6166.5 1700.82
  6217.7 1705.19  6238.8 1702.51  6253.9 1706.58  6269.0 1707.81  6332.2 1706.04
  6362.4 1709.56  6404.5 1710.91  6419.6 1715.15  6455.7 1717.28  6766.1 1726.79
#Mann=3,-1,0
  3950.4    0.05       0  4992.4    0.05       0  5001.8    0.05       0
Bank Sta=4992.4,5001.8
Exp/Cntr=0.3,0.1

Chan Stop Cuts=-1