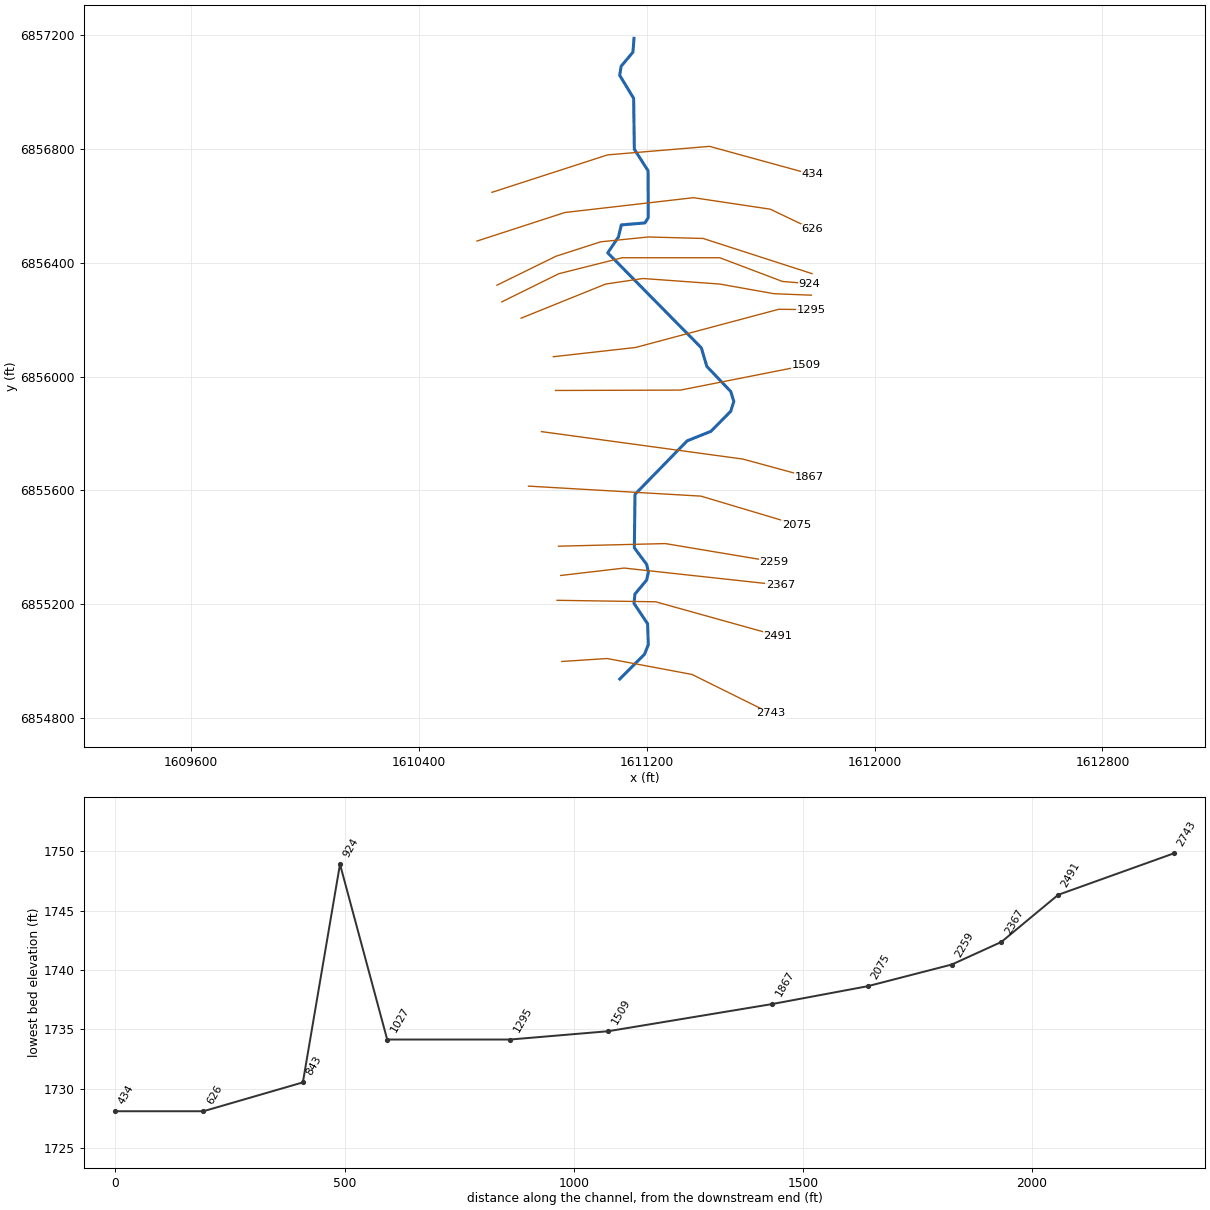
--- Elm 02 35.prj (project) ---

Proj Title=Elm 02 35 Base Level Engineering
Current Plan=p01
Default Exp/Contr=0.3,0.1
English Units
Geom File=g01
Flow File=f01
Plan File=p01
BEGIN DESCRIPTION:
Elm 02 35
END DESCRIPTION:

--- Elm 02 35.p01 (plan) ---

Plan Title=Multiple Run
Short Identifier=Multiple
Geom File=g01
Flow File=f01
Subcritical Flow
K Sum by GR= 0
Std Step Tol= 0.01
Critical Tol= 0.01
Num of Std Step Trials= 20
Max Error Tol= 0.3
Flow Tol Ratio= 0.001
Split Flow NTrial= 30
Split Flow Tol= 0.02
Split Flow Ratio= 0.02
Log Output Level= 0
Friction Slope Method= 1
Unsteady Friction Slope Method= 2
Unsteady Bridges Friction Slope Method= 1
Parabolic Critical Depth
Global Vel Dist=  1 , 1 , 1
Global Log Level= 0
CheckData=True
Encroach Param= -1, 0, 0, 0
BEGIN DESCRIPTION:
Multiple Run
END DESCRIPTION:

--- Elm 02 35.f01 (steady flow) ---

Flow Title=Multiple
Number of Profiles=7
Profile Names=10-year,25-year,50-year,1pct_min,100-year,1pct_plu,500-year
River Rch & RM= Elm 02 35,Reach-1,2743
      38      46      52      37      59      81      75
Boundary for River Rch & Prof#=Elm 02 35,Reach-1,1
Up Type=0
Dn Type=3
Dn Slope=0.001
Boundary for River Rch & Prof#=Elm 02 35,Reach-1,2
Up Type=0
Dn Type=3
Dn Slope=0.001
Boundary for River Rch & Prof#=Elm 02 35,Reach-1,3
Up Type=0
Dn Type=3
Dn Slope=0.001
Boundary for River Rch & Prof#=Elm 02 35,Reach-1,4
Up Type=0
Dn Type=3
Dn Slope=0.001
Boundary for River Rch & Prof#=Elm 02 35,Reach-1,5
Up Type=0
Dn Type=3
Dn Slope=0.001
Boundary for River Rch & Prof#=Elm 02 35,Reach-1,6
Up Type=0
Dn Type=3
Dn Slope=0.001
Boundary for River Rch & Prof#=Elm 02 35,Reach-1,7
Up Type=0
Dn Type=3
Dn Slope=0.001

--- Elm 02 35.g01 (geometry) ---

Geom Title=Existing Conditions

River Reach=Elm 02 35,Reach-1
Reach XY= 30
      1611105.00      6854938.00      1611191.76      6855024.66
      1611205.22      6855058.05      1611202.81      6855132.03
      1611155.10      6855203.40      1611158.40      6855236.28
      1611199.59      6855285.80      1611205.39      6855313.00
      1611199.62      6855340.18      1611156.24      6855398.50
      1611158.53      6855586.54      1611341.79      6855774.37
      1611425.14      6855807.77      1611494.84      6855878.30
      1611505.59      6855913.00      1611494.81      6855947.67
      1611410.87      6856035.72      1611391.37      6856101.21
      1611062.76      6856434.62      1611100.36      6856490.08
      1611110.49      6856532.71      1611193.36      6856539.65
      1611205.02      6856557.99      1611204.48      6856722.78
      1611156.22      6856798.51      1611153.76      6856977.50
      1611104.66      6857058.17      1611110.12      6857090.25
      1611151.31      6857139.49      1611155.00      6857188.00

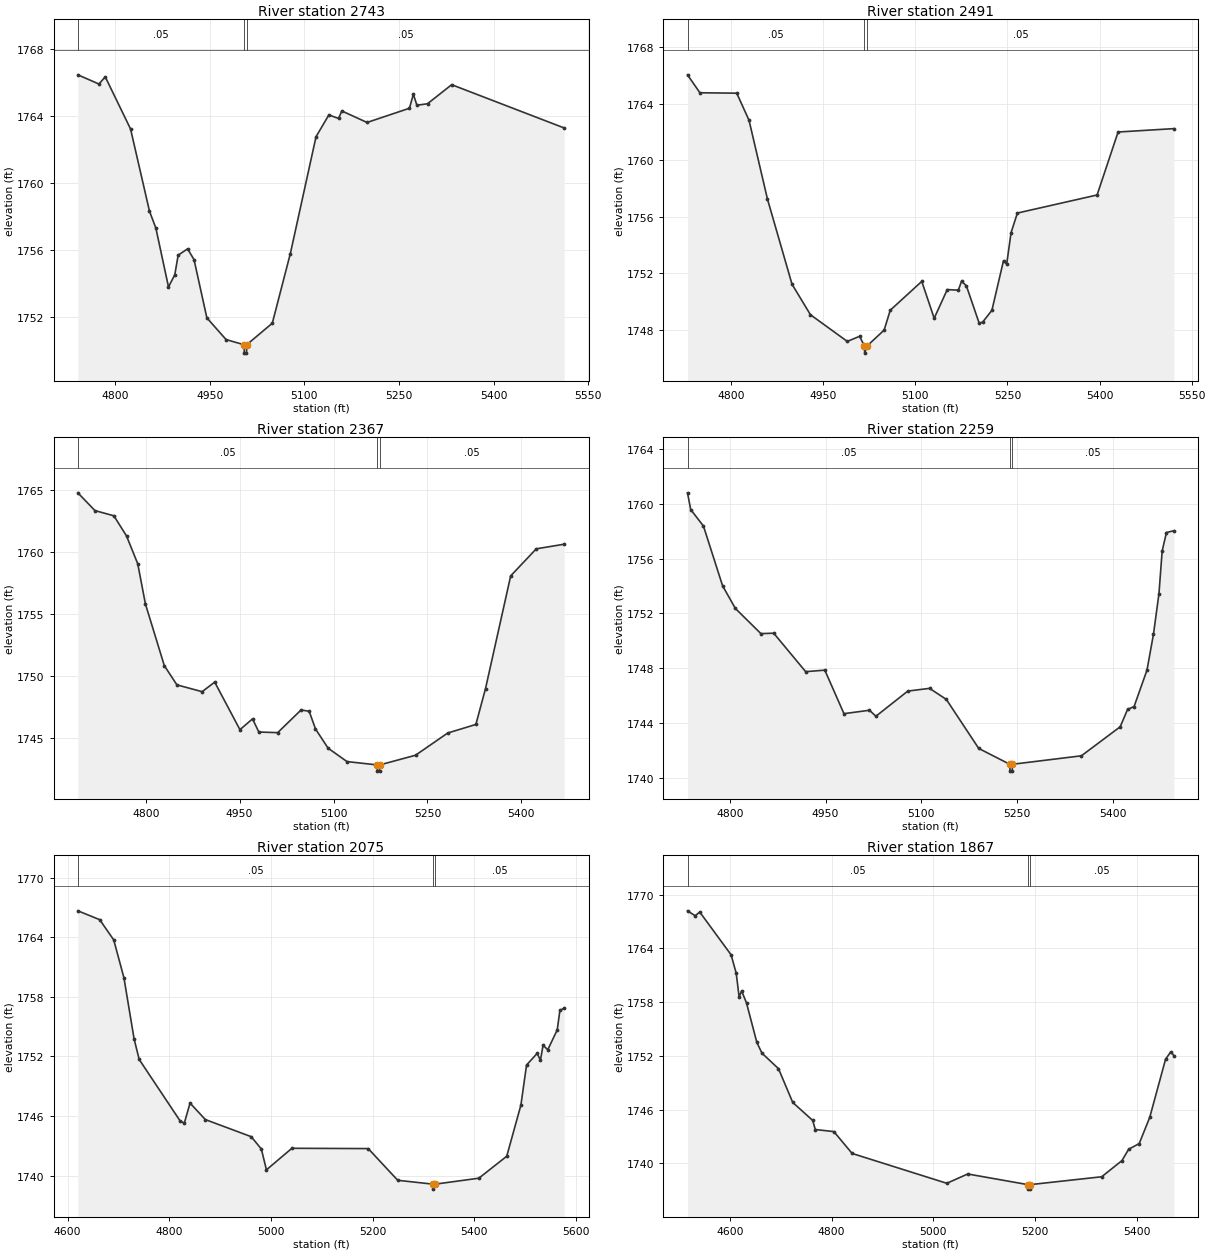
Type RM Length L Ch R = 1,2743,252,252,252
BEGIN DESCRIPTION:
Elm 02 35 2.0
END DESCRIPTION:
XS GIS Cut Line= 4
      1610901.70      6854999.46      1611060.57      6855009.88
      1611358.74      6854953.89      1611634.75      6854817.19
#Sta/Elev= 30
  4741.1 1766.48  4774.5 1765.93  4784.5 1766.36  4824.6 1763.24  4854.6 1758.32
  4864.7 1757.31  4884.7 1753.79  4894.7 1754.52  4900.0 1755.69  4915.0 1756.07
  4925.2 1755.42  4945.5 1751.94  4976.0 1750.64  5004.6 1750.33  5004.8 1749.83
  5008.3 1749.83  5008.6 1750.33  5049.2 1751.62  5077.8 1755.79  5118.5 1762.78
  5138.8 1764.08  5154.2 1763.87  5159.3 1764.32  5199.3 1763.63  5266.5 1764.48
  5272.7 1765.32  5278.3 1764.66  5295.1 1764.75  5333.4 1765.89  5511.7 1763.30
#Mann=3,-1,0
  4741.1    0.05       0  5004.6    0.03       0  5008.6    0.05       0
Bank Sta=5004.6,5008.6
Exp/Cntr=0.3,0.1

Type RM Length L Ch R = 1,2491,124,124,124
BEGIN DESCRIPTION:
Mapping XS 027d5642
END DESCRIPTION:
XS GIS Cut Line= 3
      1610884.82      6855214.30      1611231.14      6855209.10
      1611660.41      6855089.42
#Sta/Elev= 30
  4729.0 1766.05  4749.2 1764.78  4809.2 1764.75  4829.2 1762.83  4859.2 1757.25
  4899.2 1751.22  4929.2 1749.06  4989.2 1747.17  5009.2 1747.53  5017.2 1746.84
  5017.5 1746.34  5021.2 1746.84  5049.2 1747.97  5059.2 1749.38  5110.5 1751.42
  5130.7 1748.81  5152.0 1750.84  5170.1 1750.80  5175.3 1751.44  5183.2 1751.10
  5203.9 1748.47  5209.5 1748.53  5224.7 1749.37  5243.6 1752.89  5248.8 1752.65
  5255.9 1754.87  5266.2 1756.26  5396.0 1757.54  5430.2 1762.00  5521.0 1762.24
#Mann=3,-1,0
  4729.0    0.05       0  5017.2    0.03       0  5021.2    0.05       0
Bank Sta=5017.2,5021.2
Exp/Cntr=0.3,0.1

Type RM Length L Ch R = 1,2367,108,108,108
BEGIN DESCRIPTION:
Mapping XS 5cca840a
END DESCRIPTION:
XS GIS Cut Line= 3
      1610897.85      6855301.55      1611120.46      6855327.59
      1611669.98      6855267.69
#Sta/Elev= 30
  4691.6 1764.79  4718.9 1763.36  4749.1 1762.94  4769.3 1761.32  4787.3 1759.07
  4799.5 1755.84  4829.7 1750.87  4849.8 1749.32  4890.1 1748.77  4910.2 1749.54
  4950.5 1745.71  4970.6 1746.58  4980.7 1745.52  5010.8 1745.47  5048.2 1747.30
  5061.1 1747.19  5071.2 1745.77  5091.3 1744.22  5121.5 1743.14  5169.8 1742.87
  5170.0 1742.37  5173.5 1742.37  5173.8 1742.87  5231.0 1743.65  5282.4 1745.44
  5327.4 1746.13  5342.8 1749.02  5383.0 1758.10  5423.9 1760.28  5468.5 1760.65
#Mann=3,-1,0
  4691.6    0.05       0  5169.8    0.05       0  5173.8    0.05       0
Bank Sta=5169.8,5173.8
Exp/Cntr=0.3,0.1

Type RM Length L Ch R = 1,2259,184,184,184
BEGIN DESCRIPTION:
Mapping XS b7ebdc83
END DESCRIPTION:
XS GIS Cut Line= 3
      1610889.99      6855404.41      1611264.99      6855413.52
      1611646.48      6855349.73
#Sta/Elev= 30
  4733.8 1760.81  4738.8 1759.59  4758.8 1758.38  4788.8 1754.01  4808.8 1752.36
  4848.8 1750.52  4868.9 1750.55  4918.9 1747.74  4948.9 1747.85  4978.9 1744.67
  5018.9 1744.92  5028.9 1744.48  5078.9 1746.32  5113.0 1746.52  5139.3 1745.71
  5190.0 1742.13  5238.7 1740.97  5239.0 1740.47  5242.5 1740.47  5242.7 1740.97
  5350.9 1741.59  5411.6 1743.71  5423.2 1744.98  5433.4 1745.19  5453.6 1747.85
  5463.8 1750.48  5472.4 1753.45  5477.4 1756.56  5484.1 1757.91  5495.7 1758.04
#Mann=3,-1,0
  4733.8    0.05       0  5238.7    0.03       0  5242.7    0.05       0
Bank Sta=5238.7,5242.7
Exp/Cntr=0.3,0.1

Type RM Length L Ch R = 1,2075,208,208,208
BEGIN DESCRIPTION:
Mapping XS bf2509b6
END DESCRIPTION:
XS GIS Cut Line= 3
      1610784.52      6855615.35      1611389.99      6855580.19
      1611725.96      6855479.92
#Sta/Elev= 30
  4620.1 1766.65  4663.1 1765.76  4690.7 1763.72  4710.7 1759.93  4730.8 1753.75
  4740.8 1751.69  4820.9 1745.54  4829.5 1745.27  4840.9 1747.30  4871.0 1745.64
  4961.2 1743.92  4981.2 1742.68  4991.2 1740.58  5041.3 1742.75  5191.5 1742.72
  5249.6 1739.53  5319.1 1739.14  5319.3 1738.64  5323.1 1739.14  5409.2 1739.74
  5464.1 1741.95  5492.0 1747.10  5503.1 1751.13  5524.0 1752.30  5530.4 1751.61
  5535.6 1753.12  5544.9 1752.67  5563.5 1754.67  5568.7 1756.62  5577.2 1756.86
#Mann=3,-1,0
  4620.1    0.05       0  5319.1    0.03       0  5323.1    0.05       0
Bank Sta=5319.1,5323.1
Exp/Cntr=0.3,0.1

Type RM Length L Ch R = 1,1867,358,358,358
BEGIN DESCRIPTION:
Mapping XS aa096eb5
END DESCRIPTION:
XS GIS Cut Line= 3
      1610830.05      6855806.76      1611537.13      6855710.40
      1611770.72      6855646.81
#Sta/Elev= 30
  4516.9 1768.19  4532.0 1767.64  4540.9 1768.06  4602.6 1763.28  4612.7 1761.21
  4618.3 1758.59  4623.3 1759.25  4632.9 1757.90  4653.1 1753.52  4663.2 1752.31
  4695.7 1750.58  4723.7 1746.81  4763.0 1744.80  4768.0 1743.79  4804.5 1743.56
  4840.4 1741.12  5026.5 1737.79  5067.5 1738.83  5186.0 1737.64  5186.2 1737.14
  5189.7 1737.14  5190.0 1737.64  5330.8 1738.52  5370.6 1740.32  5383.8 1741.59
  5404.5 1742.22  5425.2 1745.14  5456.3 1751.63  5466.7 1752.47  5472.6 1752.04
#Mann=3,-1,0
  4516.9    0.05       0  5186.0    0.05       0  5190.0    0.05       0
Bank Sta=5186,5190
Exp/Cntr=0.3,0.1

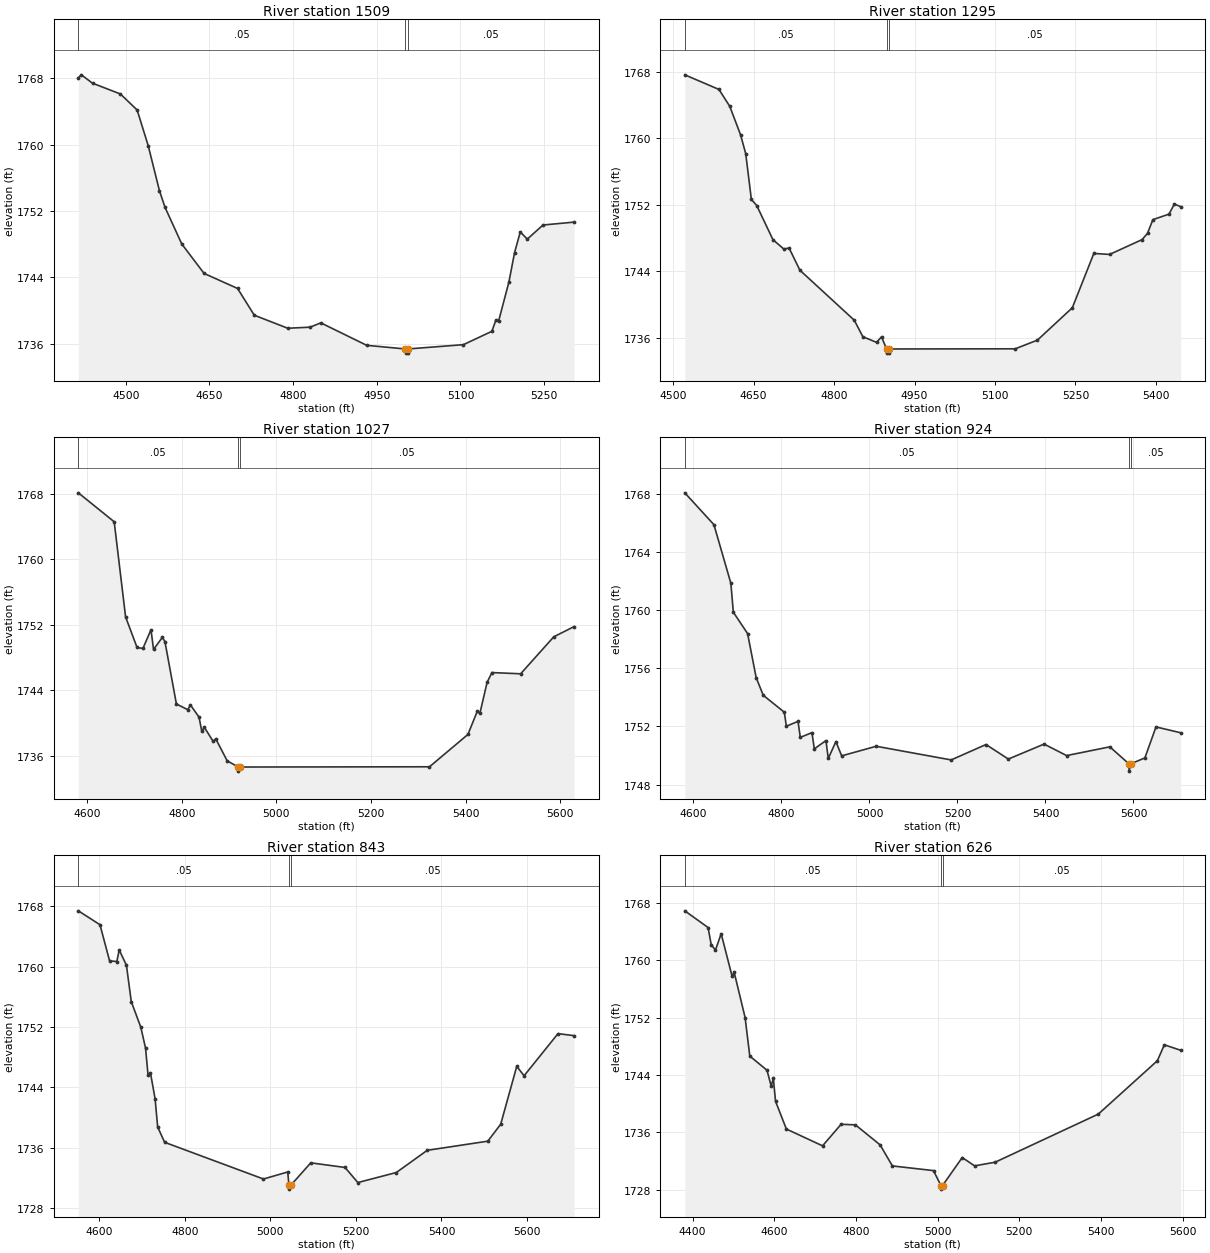
Type RM Length L Ch R = 1,1509,214,214,214
BEGIN DESCRIPTION:
Mapping XS 2f6ce8ea
END DESCRIPTION:
XS GIS Cut Line= 3
      1610879.58      6855951.28      1611318.38      6855952.59
      1611759.74      6856039.82
#Sta/Elev= 30
  4415.1 1768.04  4420.5 1768.41  4440.5 1767.40  4490.5 1766.10  4520.5 1764.17
  4540.5 1759.83  4560.5 1754.43  4570.5 1752.43  4600.5 1748.01  4640.5 1744.46
  4700.5 1742.65  4730.5 1739.42  4790.5 1737.85  4830.5 1737.98  4849.7 1738.50
  4932.0 1735.79  5001.4 1735.35  5001.6 1734.85  5005.1 1734.85  5005.4 1735.35
  5105.3 1735.87  5156.3 1737.48  5163.4 1738.81  5168.5 1738.74  5186.8 1743.41
  5197.0 1746.97  5207.2 1749.46  5219.8 1748.60  5248.0 1750.30  5303.8 1750.65
#Mann=3,-1,0
  4415.1    0.05       0  5001.4    0.03       0  5005.4    0.05       0
Bank Sta=5001.4,5005.4
Exp/Cntr=0.3,0.1

Type RM Length L Ch R = 1,1295,268,268,268
BEGIN DESCRIPTION:
Mapping XS 9320682d
END DESCRIPTION:
XS GIS Cut Line= 4
      1610871.72      6856069.77      1611160.83      6856102.33
      1611663.43      6856236.44      1611776.70      6856235.14
#Sta/Elev= 30
  4521.7 1767.65  4585.4 1765.89  4605.5 1763.86  4625.6 1760.44  4635.3 1758.16
  4645.8 1752.65  4655.8 1751.92  4686.0 1747.81  4706.1 1746.69  4716.2 1746.79
  4736.3 1744.13  4837.7 1738.11  4853.6 1736.13  4879.1 1735.45  4888.5 1736.11
  4897.8 1734.65  4898.0 1734.15  4901.5 1734.15  4901.8 1734.65  5137.8 1734.67
  5179.2 1735.72  5244.2 1739.61  5284.3 1746.15  5313.7 1746.03  5374.4 1747.82
  5384.4 1748.58  5394.4 1750.22  5424.4 1750.88  5434.4 1752.09  5446.1 1751.79
#Mann=3,-1,0
  4521.7    0.05       0  4897.8    0.03       0  4901.8    0.05       0
Bank Sta=4897.8,4901.8
Exp/Cntr=0.3,0.1

Type RM Length L Ch R = 1,1027,103,103,103
BEGIN DESCRIPTION:
Mapping XS ba036564
END DESCRIPTION:
XS GIS Cut Line= 6
      1610758.44      6856205.18      1611055.36      6856324.98
      1611186.87      6856344.51      1611456.40      6856324.98
      1611646.50      6856291.13      1611778.04      6856285.92
#Sta/Elev= 30
  4581.4 1768.09  4657.2 1764.56  4681.3 1752.96  4705.5 1749.23  4717.9 1749.11
  4735.0 1751.39  4740.4 1748.99  4759.1 1750.47  4764.5 1749.94  4788.7 1742.34
  4812.8 1741.64  4818.2 1742.23  4836.5 1740.74  4842.4 1739.00  4847.7 1739.50
  4866.5 1737.77  4871.9 1738.09  4896.0 1735.41  4919.4 1734.65  4919.7 1734.15
  4923.4 1734.65  5323.7 1734.68  5404.9 1738.62  5425.1 1741.50  5430.2 1741.19
  5445.5 1744.98  5455.7 1746.17  5516.4 1746.02  5586.4 1750.53  5629.5 1751.78
#Mann=3,-1,0
  4581.4    0.05       0  4919.4    0.05       0  4923.4    0.05       0
Bank Sta=4919.4,4923.4
Exp/Cntr=0.3,0.1

Type RM Length L Ch R = 1,924,81,81,81
BEGIN DESCRIPTION:
Mapping XS 571ec5c3
END DESCRIPTION:
XS GIS Cut Line= 6
      1610690.80      6856262.49      1610891.30      6856361.44
      1611113.95      6856417.43      1611456.40      6856417.43
      1611676.45      6856334.10      1611770.79      6856326.34
#Sta/Elev= 30
  4580.3 1768.06  4646.5 1765.87  4685.0 1761.84  4690.6 1759.85  4723.0 1758.38
  4742.5 1755.35  4758.5 1754.14  4806.5 1752.97  4811.1 1752.01  4837.6 1752.34
  4842.8 1751.24  4869.3 1751.57  4874.6 1750.45  4901.1 1751.02  4906.3 1749.79
  4923.7 1750.95  4936.8 1749.97  5015.3 1750.63  5185.6 1749.69  5264.8 1750.75
  5315.6 1749.75  5396.8 1750.78  5448.0 1749.99  5546.2 1750.59  5589.7 1749.42
  5589.9 1748.92  5593.7 1749.42  5625.9 1749.83  5651.1 1751.96  5707.1 1751.56
#Mann=3,-1,0
  4580.3    0.05       0  5589.7    0.05       0  5593.7    0.05       0
Bank Sta=5589.7,5593.7
Exp/Cntr=0.3,0.1

Type RM Length L Ch R = 1,843,217,217,217
BEGIN DESCRIPTION:
Mapping XS 0b979cb9
END DESCRIPTION:
XS GIS Cut Line= 6
      1610673.84      6856321.07      1610880.88      6856422.64
      1611038.43      6856473.42      1611205.10      6856490.35
      1611397.81      6856485.14      1611780.33      6856361.55
#Sta/Elev= 30
  4550.8 1767.39  4601.4 1765.55  4623.9 1760.76  4640.8 1760.68  4646.4 1762.21
  4663.3 1760.18  4674.6 1755.37  4696.9 1751.98  4708.0 1749.20  4713.9 1745.59
  4719.4 1745.96  4730.3 1742.50  4736.3 1738.77  4752.6 1736.74  4983.7 1731.88
  5040.4 1732.81  5043.4 1731.04  5043.6 1730.54  5047.4 1731.04  5094.3 1734.02
  5174.4 1733.41  5204.4 1731.41  5294.4 1732.74  5366.7 1735.68  5508.3 1736.89
  5538.4 1739.13  5576.0 1746.80  5593.1 1745.55  5672.4 1751.13  5710.2 1750.86
#Mann=3,-1,0
  4550.8    0.05       0  5043.4    0.03       0  5047.4    0.05       0
Bank Sta=5043.4,5047.4
Exp/Cntr=0.3,0.1

Type RM Length L Ch R = 1,626,192,192,192
BEGIN DESCRIPTION:
Mapping XS 2b95644b
END DESCRIPTION:
XS GIS Cut Line= 5
      1610603.56      6856476.03      1610912.13      6856576.28
      1611363.95      6856628.37      1611633.48      6856588.00
      1611780.29      6856517.85
#Sta/Elev= 30
  4380.9 1766.87  4438.0 1764.54  4445.5 1762.16  4456.0 1761.40  4470.0 1763.68
  4496.7 1757.76  4501.9 1758.30  4528.6 1752.01  4540.1 1746.64  4582.2 1744.67
  4592.5 1742.46  4597.8 1743.52  4603.2 1740.34  4629.7 1736.48  4718.3 1734.14
  4763.8 1737.14  4798.8 1737.06  4859.2 1734.28  4889.4 1731.34  4990.1 1730.69
  5008.2 1728.61  5008.5 1728.11  5012.2 1728.61  5060.5 1732.51  5090.7 1731.35
  5141.1 1731.86  5393.8 1738.56  5538.4 1745.99  5555.5 1748.21  5595.4 1747.45
#Mann=3,-1,0
  4380.9    0.05       0  5008.2    0.03       0  5012.2    0.05       0
Bank Sta=5008.2,5012.2
Exp/Cntr=0.3,0.1

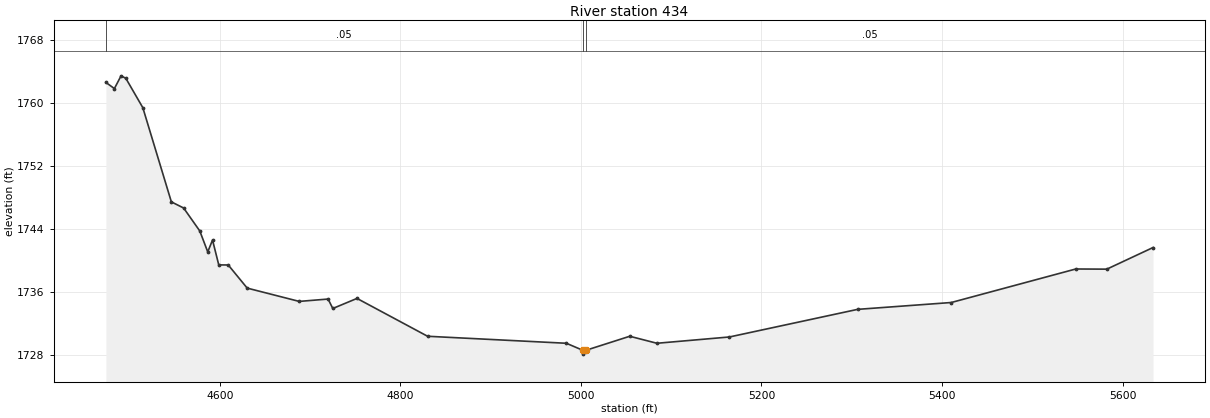
Type RM Length L Ch R = 1,434,0,0,0
BEGIN DESCRIPTION:
Elm 02 35 1.0
END DESCRIPTION:
XS GIS Cut Line= 4
      1610656.07      6856647.14      1611062.30      6856778.65
      1611420.38      6856808.60      1611780.55      6856709.78
#Sta/Elev= 30
  4473.9 1762.64  4483.3 1761.86  4490.7 1763.48  4496.0 1763.16  4514.8 1759.43
  4546.4 1747.46  4560.0 1746.68  4577.9 1743.76  4586.7 1741.10  4592.0 1742.61
  4598.9 1739.45  4609.4 1739.44  4630.4 1736.50  4688.0 1734.81  4720.0 1735.11
  4725.2 1733.91  4752.0 1735.19  4830.2 1730.38  4983.9 1729.49  5001.9 1728.61
  5002.2 1728.11  5005.9 1728.61  5054.1 1730.38  5084.2 1729.49  5164.5 1730.29
  5306.5 1733.80  5410.2 1734.67  5548.1 1738.93  5582.5 1738.91  5633.7 1741.66
#Mann=3,-1,0
  4473.9    0.05       0  5001.9    0.03       0  5005.9    0.05       0
Bank Sta=5001.9,5005.9
Exp/Cntr=0.3,0.1

Chan Stop Cuts=-1