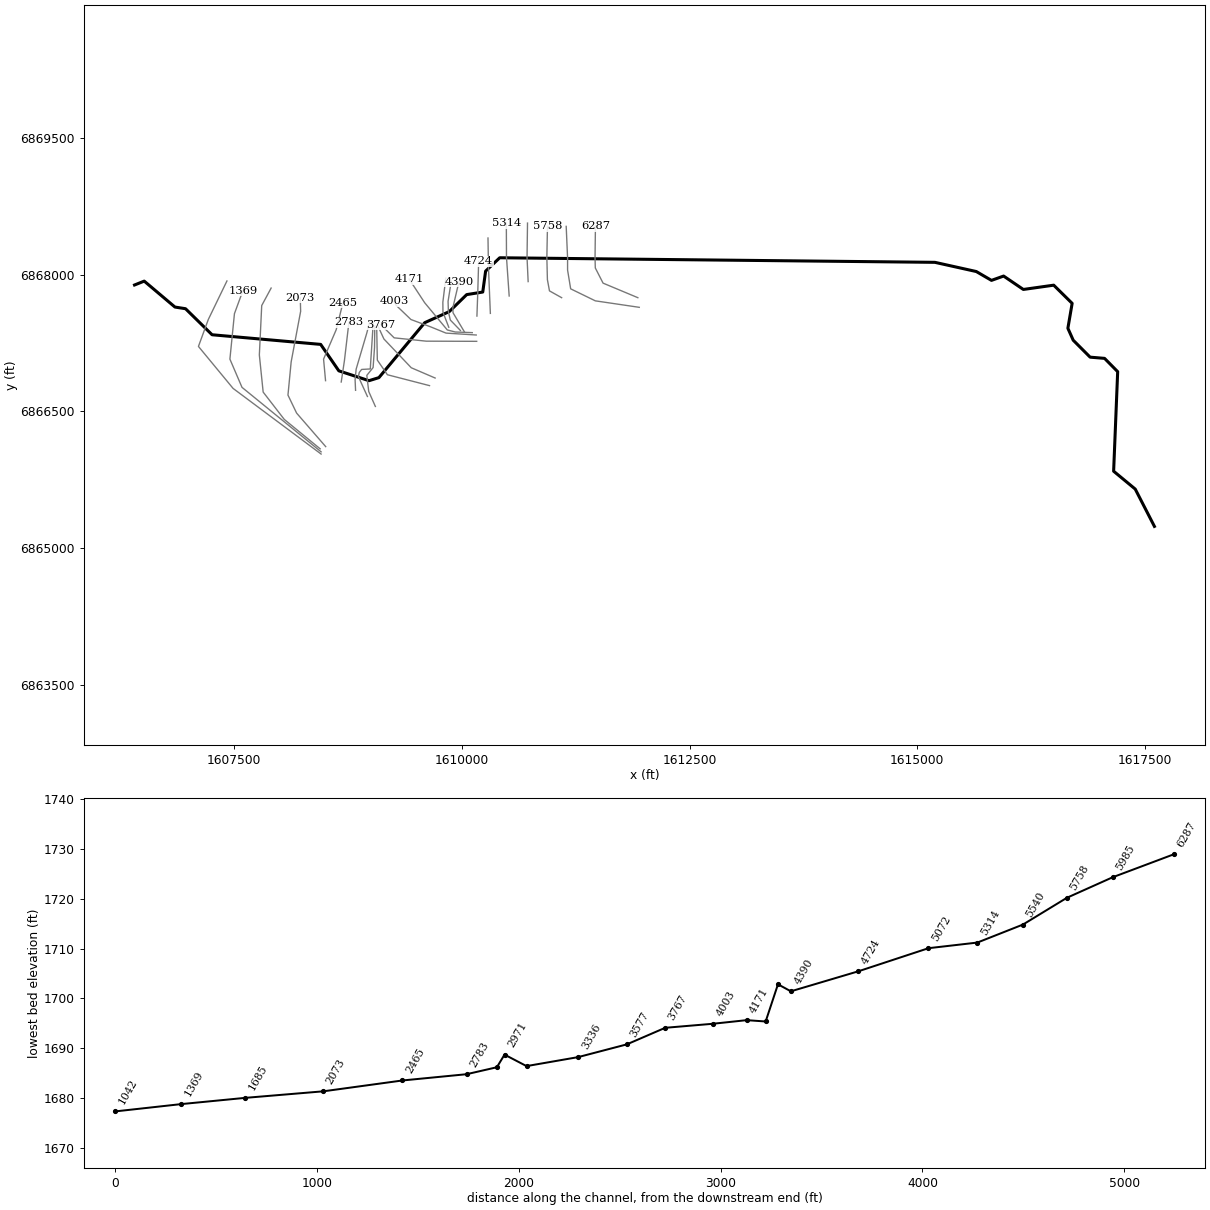
--- Elm 02 38.prj (project) ---

Proj Title=Elm 02 38 Base Level Engineering
Current Plan=p01
Default Exp/Contr=0.3,0.1
English Units
Geom File=g01
Flow File=f01
Plan File=p01
Y Axis Title=Elevation
X Axis Title(PF)=Main Channel Distance
X Axis Title(XS)=Station
BEGIN DESCRIPTION:
Elm 02 38
END DESCRIPTION:
DSS Export Rating Curves= 0
DSS Export Rating Curve Sorted= 0
DSS Export Volume Flow Curves= 0
DXF OffsetX= 0
DXF OffsetY= 0
DXF ScaleX= 1
DXF ScaleY= 10

--- Elm 02 38.p01 (plan) ---

Plan Title=Multiple Run
Short Identifier=Multiple
Geom File=g01
Flow File=f01
Subcritical Flow
K Sum by GR= 0
Std Step Tol= 0.01
Critical Tol= 0.01
Num of Std Step Trials= 20
Max Error Tol= 0.3
Flow Tol Ratio= 0.001
Split Flow NTrial= 30
Split Flow Tol= 0.02
Split Flow Ratio= 0.02
Log Output Level= 0
Friction Slope Method= 1
Unsteady Friction Slope Method= 2
Unsteady Bridges Friction Slope Method= 1
Parabolic Critical Depth
Global Vel Dist=  1 , 1 , 1
Global Log Level= 0
CheckData=True
Encroach Param= -1, 0, 0, 0
BEGIN DESCRIPTION:
Multiple Run
END DESCRIPTION:

--- Elm 02 38.f01 (steady flow) ---

Flow Title=Multiple
Number of Profiles=7
Profile Names=10-year,25-year,50-year,1pct_min,100-year,1pct_plu,500-year
River Rch & RM= Elm 02 38,Reach-1,6287
     272     374     457     346     554     763     827
River Rch & RM= Elm 02 38,Reach-1,3080
     353     495     614     471     754    1040    1150
Boundary for River Rch & Prof#=Elm 02 38,Reach-1,1
Up Type=0
Dn Type=3
Dn Slope=0.001
Boundary for River Rch & Prof#=Elm 02 38,Reach-1,2
Up Type=0
Dn Type=3
Dn Slope=0.001
Boundary for River Rch & Prof#=Elm 02 38,Reach-1,3
Up Type=0
Dn Type=3
Dn Slope=0.001
Boundary for River Rch & Prof#=Elm 02 38,Reach-1,4
Up Type=0
Dn Type=3
Dn Slope=0.001
Boundary for River Rch & Prof#=Elm 02 38,Reach-1,5
Up Type=0
Dn Type=3
Dn Slope=0.001
Boundary for River Rch & Prof#=Elm 02 38,Reach-1,6
Up Type=0
Dn Type=3
Dn Slope=0.001
Boundary for River Rch & Prof#=Elm 02 38,Reach-1,7
Up Type=0
Dn Type=3
Dn Slope=0.001

--- Elm 02 38.g01 (geometry) ---

Geom Title=Existing Conditions

River Reach=Elm 02 38,Reach-1
Reach XY= 30
      1617605.00      6865238.00      1617394.24      6865647.70
      1617157.05      6865843.84      1617201.47      6866936.54
      1617057.45      6867082.53      1616898.81      6867095.82
      1616713.14      6867281.94      1616654.59      6867413.00
      1616701.47      6867686.53      1616499.11      6867886.04
      1616165.44      6867839.05      1615948.89      6867986.20
      1615815.69      6867938.75      1615649.07      6868035.75
      1615194.50      6868136.78      1610415.43      6868186.95
      1610260.46      6868040.45      1610229.03      6867810.65
      1610052.55      6867782.53      1609861.17      6867595.86
      1609591.79      6867474.37      1609088.58      6866871.08
      1608979.80      6866837.52      1608648.48      6866945.68
      1608449.14      6867235.93      1607256.55      6867341.75
      1606965.10      6867627.61      1606848.83      6867645.86
      1606511.37      6867930.60      1606405.00      6867888.00

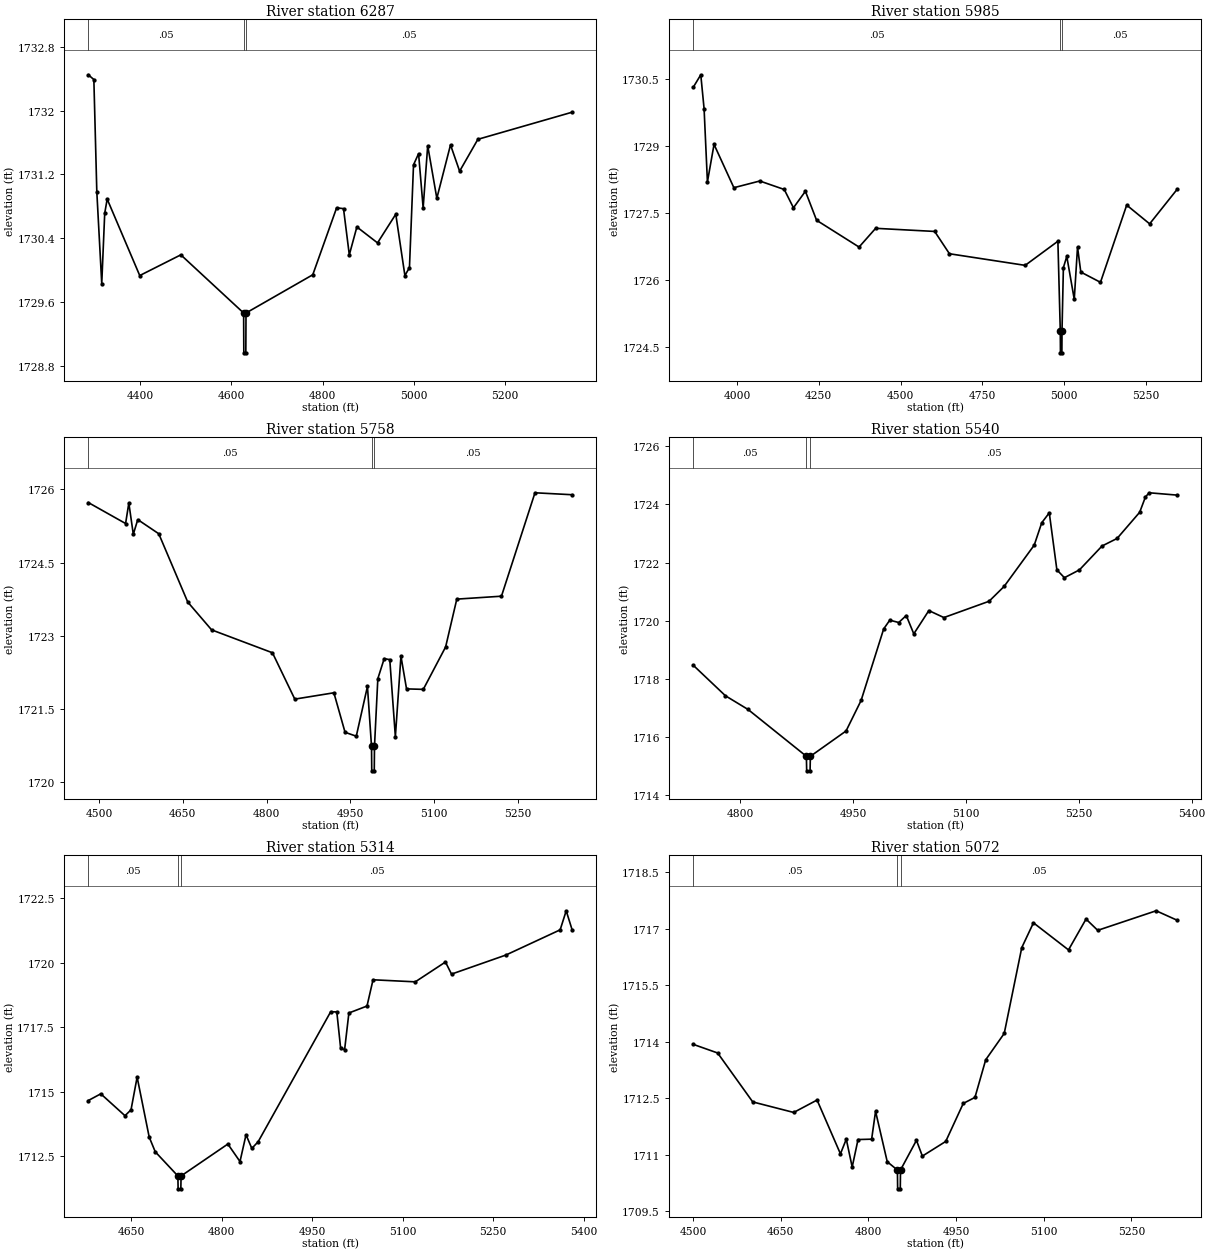
Type RM Length L Ch R = 1,6287,302,302,302
BEGIN DESCRIPTION:
Elm 02 38 6286.74
END DESCRIPTION:
XS GIS Cut Line= 5
      1611932.22      6867748.72      1611550.24      6867908.46
      1611464.88      6868075.24      1611462.13      6868190.85
      1611466.45      6868534.49
#Sta/Elev= 30
  4286.1 1732.45  4298.3 1732.39  4304.8 1730.98  4315.6 1729.83  4322.1 1730.71
  4327.5 1730.89  4398.9 1729.93  4489.0 1730.19  4626.7 1729.46  4627.1 1728.96
  4631.5 1728.96  4631.9 1729.46  4778.3 1729.94  4830.6 1730.78  4845.7 1730.77
  4858.4 1730.19  4875.0 1730.54  4920.3 1730.34  4960.3 1730.70  4980.3 1729.93
  4990.3 1730.03  4999.2 1731.32  5010.3 1731.46  5020.3 1730.78  5030.3 1731.56
  5050.3 1730.90  5080.3 1731.57  5100.3 1731.24  5140.3 1731.64  5346.8 1731.98
#Mann=3,-1,0
  4286.1    0.05       0  4626.7    0.03       0  4631.9    0.05       0
Bank Sta=4626.7,4631.9
Exp/Cntr=0.3,0.1

Type RM Length L Ch R = 1,5985,227,227,227
BEGIN DESCRIPTION:
Elm 02 38 5984.97
END DESCRIPTION:
XS GIS Cut Line= 6
      1611947.79      6867642.84      1611465.17      6867714.01
      1611194.34      6867845.96      1611160.48      6868052.56
      1611160.48      6868186.51      1611145.29      6868531.57
#Sta/Elev= 30
  3866.6 1730.31  3889.6 1730.59  3899.7 1729.83  3909.9 1728.19  3930.1 1729.03
  3990.7 1728.06  4069.9 1728.21  4144.6 1728.02  4172.7 1727.61  4209.2 1727.98
  4243.4 1727.33  4373.1 1726.73  4423.8 1727.15  4604.1 1727.08  4649.2 1726.58
  4880.5 1726.32  4980.5 1726.86  4987.8 1724.86  4988.3 1724.36  4992.7 1724.36
  4993.1 1724.86  4997.3 1726.27  5007.7 1726.52  5030.5 1725.56  5040.5 1726.73
  5050.5 1726.17  5110.6 1725.94  5190.7 1727.67  5260.8 1727.25  5344.4 1728.02
#Mann=3,-1,0
  3866.6    0.05       0  4987.8    0.03       0  4993.1    0.05       0
Bank Sta=4987.8,4993.1
Exp/Cntr=0.3,0.1

Type RM Length L Ch R = 1,5758,218,218,218
BEGIN DESCRIPTION:
Elm 02 38 5757.51
END DESCRIPTION:
XS GIS Cut Line= 5
      1611095.37      6867748.74      1610961.70      6867823.39
      1610938.96      6867946.69      1610932.91      6868190.27
      1610939.82      6868534.36
#Sta/Elev= 30
  4480.8 1725.73  4547.6 1725.30  4553.4 1725.72  4561.4 1725.08  4569.4 1725.38
  4607.0 1725.09  4658.9 1723.69  4701.6 1723.12  4810.6 1722.65  4850.6 1721.70
  4920.6 1721.83  4940.6 1721.02  4960.7 1720.94  4980.7 1721.96  4988.0 1720.73
  4988.4 1720.23  4992.9 1720.23  4993.3 1720.73  4999.3 1722.12  5010.7 1722.53
  5020.7 1722.51  5030.7 1720.93  5040.7 1722.58  5050.7 1721.91  5080.7 1721.90
  5120.7 1722.77  5140.7 1723.75  5220.7 1723.81  5280.7 1725.93  5347.1 1725.89
#Mann=3,-1,0
  4480.8    0.05       0  4988.0    0.03       0  4993.3    0.05       0
Bank Sta=4988,4993.3
Exp/Cntr=0.3,0.1

Type RM Length L Ch R = 1,5540,226,226,226
BEGIN DESCRIPTION:
Elm 02 38 5539.95
END DESCRIPTION:
XS GIS Cut Line= 3
      1610727.48      6867925.25      1610715.33      6868189.17
      1610720.54      6868567.63
#Sta/Elev= 30
  4737.8 1718.47  4780.6 1717.42  4810.6 1716.95  4888.1 1715.34  4888.5 1714.84
  4893.0 1714.84  4893.4 1715.34  4940.8 1716.21  4960.8 1717.26  4990.8 1719.72
  4998.9 1720.02  5010.8 1719.94  5020.8 1720.18  5030.8 1719.55  5050.8 1720.35
  5070.8 1720.11  5130.8 1720.67  5150.8 1721.18  5190.8 1722.60  5200.8 1723.37
  5210.8 1723.71  5220.9 1721.75  5230.9 1721.48  5250.9 1721.75  5280.9 1722.57
  5300.9 1722.83  5330.9 1723.73  5338.6 1724.26  5343.6 1724.40  5380.5 1724.32
#Mann=3,-1,0
  4737.8    0.05       0  4888.1    0.03       0  4893.4    0.05       0
Bank Sta=4888.1,4893.4
Exp/Cntr=0.3,0.1

Type RM Length L Ch R = 1,5314,242,242,242
BEGIN DESCRIPTION:
Elm 02 38 5314.44
END DESCRIPTION:
XS GIS Cut Line= 3
      1610519.15      6867767.32      1610489.63      6868190.91
      1610487.90      6868567.69
#Sta/Elev= 30
  4579.3 1714.65  4600.0 1714.91  4640.1 1714.06  4650.1 1714.29  4660.2 1715.56
  4680.2 1713.23  4690.2 1712.66  4727.7 1711.72  4728.1 1711.22  4732.6 1711.22
  4733.0 1711.72  4810.5 1712.96  4830.6 1712.28  4840.6 1713.32  4850.2 1712.79
  4860.7 1713.05  4980.9 1718.10  4991.0 1718.09  4997.3 1716.69  5003.9 1716.62
  5011.0 1718.05  5041.0 1718.32  5051.0 1719.34  5121.0 1719.26  5171.0 1720.03
  5181.0 1719.56  5271.0 1720.30  5361.0 1721.28  5371.0 1722.02  5380.7 1721.29
#Mann=3,-1,0
  4579.3    0.05       0  4727.7    0.03       0  4733.0    0.05       0
Bank Sta=4727.7,4733
Exp/Cntr=0.3,0.1

Type RM Length L Ch R = 1,5072,348,348,348
BEGIN DESCRIPTION:
Elm 02 38 5072.31
END DESCRIPTION:
XS GIS Cut Line= 3
      1610312.55      6867576.28      1610291.72      6868079.80
      1610286.52      6868403.71
#Sta/Elev= 30
  4500.3 1713.93  4542.1 1713.70  4602.1 1712.40  4672.2 1712.12  4712.2 1712.45
  4752.2 1711.02  4762.2 1711.41  4772.3 1710.67  4782.3 1711.40  4805.6 1711.41
  4812.3 1712.15  4832.3 1710.81  4849.7 1710.59  4850.1 1710.09  4854.6 1710.09
  4855.0 1710.59  4882.3 1711.38  4892.4 1710.96  4932.4 1711.35  4962.4 1712.36
  4982.4 1712.52  5000.8 1713.52  5032.5 1714.22  5062.5 1716.50  5082.5 1717.16
  5142.5 1716.44  5172.5 1717.26  5192.5 1716.96  5292.5 1717.48  5328.2 1717.23
#Mann=3,-1,0
  4500.3    0.05       0  4849.7    0.03       0  4855.0    0.05       0
Bank Sta=4849.7,4855
Exp/Cntr=0.3,0.1

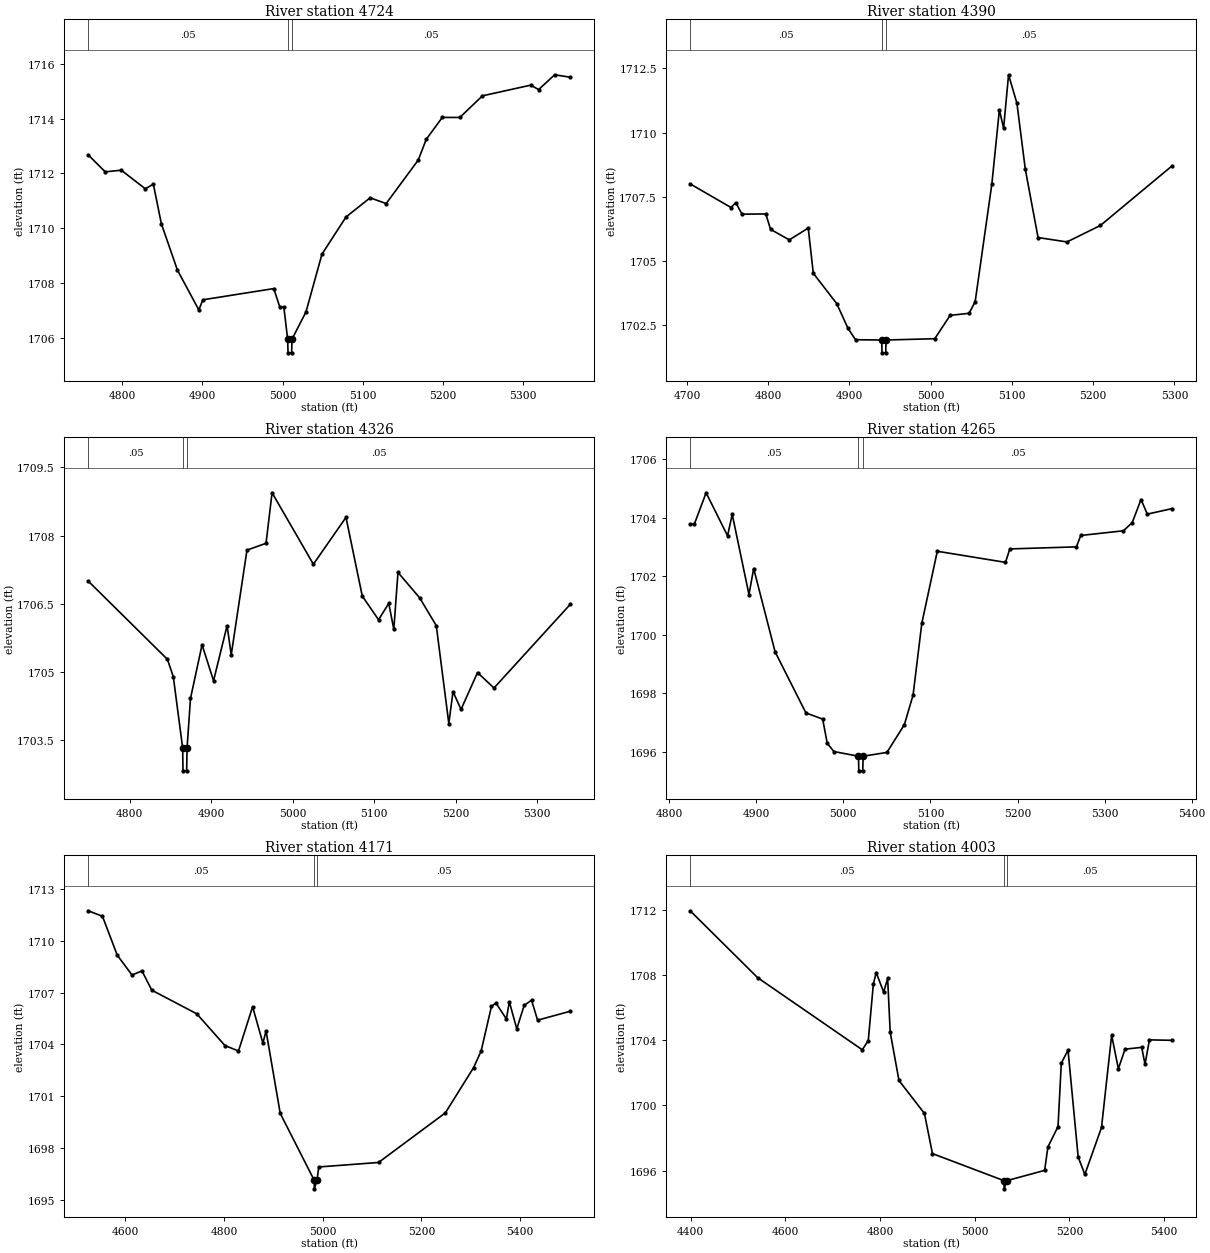
Type RM Length L Ch R = 1,4724,334,334,334
BEGIN DESCRIPTION:
Elm 02 38 4724.38
END DESCRIPTION:
XS GIS Cut Line= 3
      1610164.98      6867546.81      1610173.66      6867788.13
      1610184.08      6868147.51
#Sta/Elev= 30
  4757.8 1712.68  4779.0 1712.06  4799.0 1712.12  4829.0 1711.44  4839.0 1711.61
  4849.0 1710.16  4869.1 1708.46  4895.7 1707.01  4900.7 1707.38  4989.1 1707.79
  4996.7 1707.11  5001.7 1707.11  5006.4 1705.94  5006.9 1705.44  5011.4 1705.44
  5011.8 1705.94  5029.2 1706.93  5049.2 1709.05  5079.2 1710.41  5109.2 1711.11
  5129.2 1710.90  5169.2 1712.49  5179.2 1713.25  5199.2 1714.05  5221.1 1714.05
  5249.2 1714.84  5309.3 1715.23  5319.3 1715.07  5339.3 1715.61  5358.8 1715.52
#Mann=3,-1,0
  4757.8    0.05       0  5006.4    0.03       0  5011.8    0.05       0
Bank Sta=5006.4,5011.8
Exp/Cntr=0.3,0.1

Type RM Length L Ch R = 1,4390,64,64,64
BEGIN DESCRIPTION:
Elm 02 38 4390.25
END DESCRIPTION:
XS GIS Cut Line= 4
      1610027.76      6867373.18      1609902.74      6867582.84
      1609900.14      6867636.22      1609967.59      6867924.18
#Sta/Elev= 30
  4704.0 1708.00  4754.3 1707.08  4760.1 1707.27  4767.8 1706.82  4797.1 1706.83
  4802.9 1706.23  4826.0 1705.82  4849.3 1706.28  4855.5 1704.52  4884.3 1703.34
  4898.3 1702.37  4907.5 1701.93  4939.7 1701.92  4940.1 1701.42  4944.6 1701.42
  4945.1 1701.92  5005.0 1701.97  5023.9 1702.88  5047.2 1702.96  5054.7 1703.41
  5075.3 1708.01  5084.5 1710.88  5089.7 1710.17  5095.8 1712.25  5106.1 1711.14
  5116.4 1708.57  5132.1 1705.91  5167.7 1705.74  5208.8 1706.38  5297.3 1708.71
#Mann=3,-1,0
  4704.0    0.05       0  4939.7    0.05       0  4945.1    0.05       0
Bank Sta=4939.7,4945.1
Exp/Cntr=0.3,0.1

Type RM Length L Ch R = 1,4326,61,61,61
BEGIN DESCRIPTION:
Elm 02 38 4325.59
END DESCRIPTION:
XS GIS Cut Line= 5
      1609983.46      6867388.83      1609872.79      6867503.41
      1609851.96      6867593.25      1609848.05      6867707.84
      1609883.21      6867930.51
#Sta/Elev= 30
  4749.0 1707.00  4846.2 1705.28  4853.4 1704.90  4864.9 1703.33  4865.3 1702.83
  4869.8 1702.83  4870.3 1703.33  4874.5 1704.42  4888.7 1705.60  4902.8 1704.81
  4919.4 1706.02  4924.5 1705.38  4943.8 1707.68  4967.2 1707.83  4974.6 1708.94
  5025.3 1707.37  5065.3 1708.40  5085.3 1706.67  5105.3 1706.15  5117.8 1706.51
  5124.0 1705.94  5129.1 1707.19  5155.8 1706.63  5176.1 1706.02  5191.5 1703.87
  5196.6 1704.57  5206.5 1704.18  5226.7 1704.99  5246.9 1704.65  5340.6 1706.49
#Mann=3,-1,0
  4749.0    0.05       0  4864.9    0.03       0  4870.3    0.05       0
Bank Sta=4864.9,4870.3
Exp/Cntr=0.3,0.1

Type RM Length L Ch R = 1,4265,94,94,94
BEGIN DESCRIPTION:
Elm 02 38 4265.37
END DESCRIPTION:
XS GIS Cut Line= 4
      1609855.85      6867424.03      1609792.07      6867589.35
      1609790.76      6867698.72      1609823.23      6867963.66
#Sta/Elev= 30
  4824.2 1703.79  4829.0 1703.79  4842.5 1704.86  4867.1 1703.39  4872.5 1704.12
  4891.7 1701.38  4897.1 1702.27  4921.7 1699.42  4957.1 1697.33  4976.3 1697.12
  4981.6 1696.29  4989.2 1696.01  5017.4 1695.85  5017.8 1695.35  5022.3 1695.35
  5022.8 1695.85  5050.1 1695.98  5070.1 1696.93  5080.1 1697.94  5090.1 1700.39
  5107.9 1702.86  5186.2 1702.48  5191.2 1702.94  5267.6 1703.01  5272.6 1703.40
  5321.6 1703.56  5331.7 1703.84  5341.8 1704.63  5349.0 1704.13  5377.7 1704.32
#Mann=3,-1,0
  4824.2    0.05       0  5017.4    0.03       0  5022.8    0.05       0
Bank Sta=5017.4,5022.8
Exp/Cntr=0.3,0.1

Type RM Length L Ch R = 1,4171,168,168,168
BEGIN DESCRIPTION:
Mapping XS 83c31336
END DESCRIPTION:
XS GIS Cut Line= 5
      1610113.85      6867365.10      1609926.34      6867372.05
      1609839.53      6867394.62      1609591.27      6867693.23
      1609420.46      6867953.75
#Sta/Elev= 30
  4524.7 1711.76  4553.6 1711.44  4583.6 1709.18  4613.6 1708.03  4633.6 1708.27
  4653.6 1707.15  4744.7 1705.78  4801.8 1703.94  4829.3 1703.62  4857.9 1706.19
  4878.7 1704.08  4885.2 1704.78  4913.9 1700.00  4982.7 1696.12  4983.1 1695.62
  4988.4 1696.12  4992.0 1696.89  5113.1 1697.15  5248.6 1700.03  5305.9 1702.66
  5321.0 1703.61  5342.1 1706.22  5351.2 1706.40  5372.3 1705.48  5378.2 1706.48
  5393.3 1704.91  5408.4 1706.27  5423.3 1706.57  5435.5 1705.41  5501.9 1705.93
#Mann=3,-1,0
  4524.7    0.05       0  4982.7    0.03       0  4988.4    0.05       0
Bank Sta=4982.7,4988.4
Exp/Cntr=0.3,0.1

Type RM Length L Ch R = 1,4003,236,236,236
BEGIN DESCRIPTION:
Mapping XS f7a7f67a
END DESCRIPTION:
XS GIS Cut Line= 6
      1610157.22      6867339.06      1609825.64      6867359.90
      1609658.97      6867427.60      1609440.22      6867509.20
      1609277.03      6867665.45      1609256.20      6867707.11
#Sta/Elev= 30
  4399.3 1711.93  4541.8 1707.83  4762.8 1703.41  4775.4 1703.98  4786.2 1707.46
  4792.2 1708.14  4807.8 1706.95  4816.3 1707.78  4821.7 1704.49  4840.2 1701.53
  4894.0 1699.51  4910.9 1697.05  5062.0 1695.39  5062.4 1694.89  5067.7 1695.39
  5147.8 1696.02  5154.7 1697.45  5176.1 1698.71  5183.0 1702.59  5197.2 1703.39
  5218.6 1696.85  5232.7 1695.77  5267.9 1698.65  5289.3 1704.30  5303.5 1702.25
  5317.6 1703.45  5352.8 1703.56  5359.8 1702.52  5369.1 1704.02  5417.4 1703.99
#Mann=3,-1,0
  4399.3    0.05       0  5062.0    0.03       0  5067.7    0.05       0
Bank Sta=5062,5067.7
Exp/Cntr=0.3,0.1

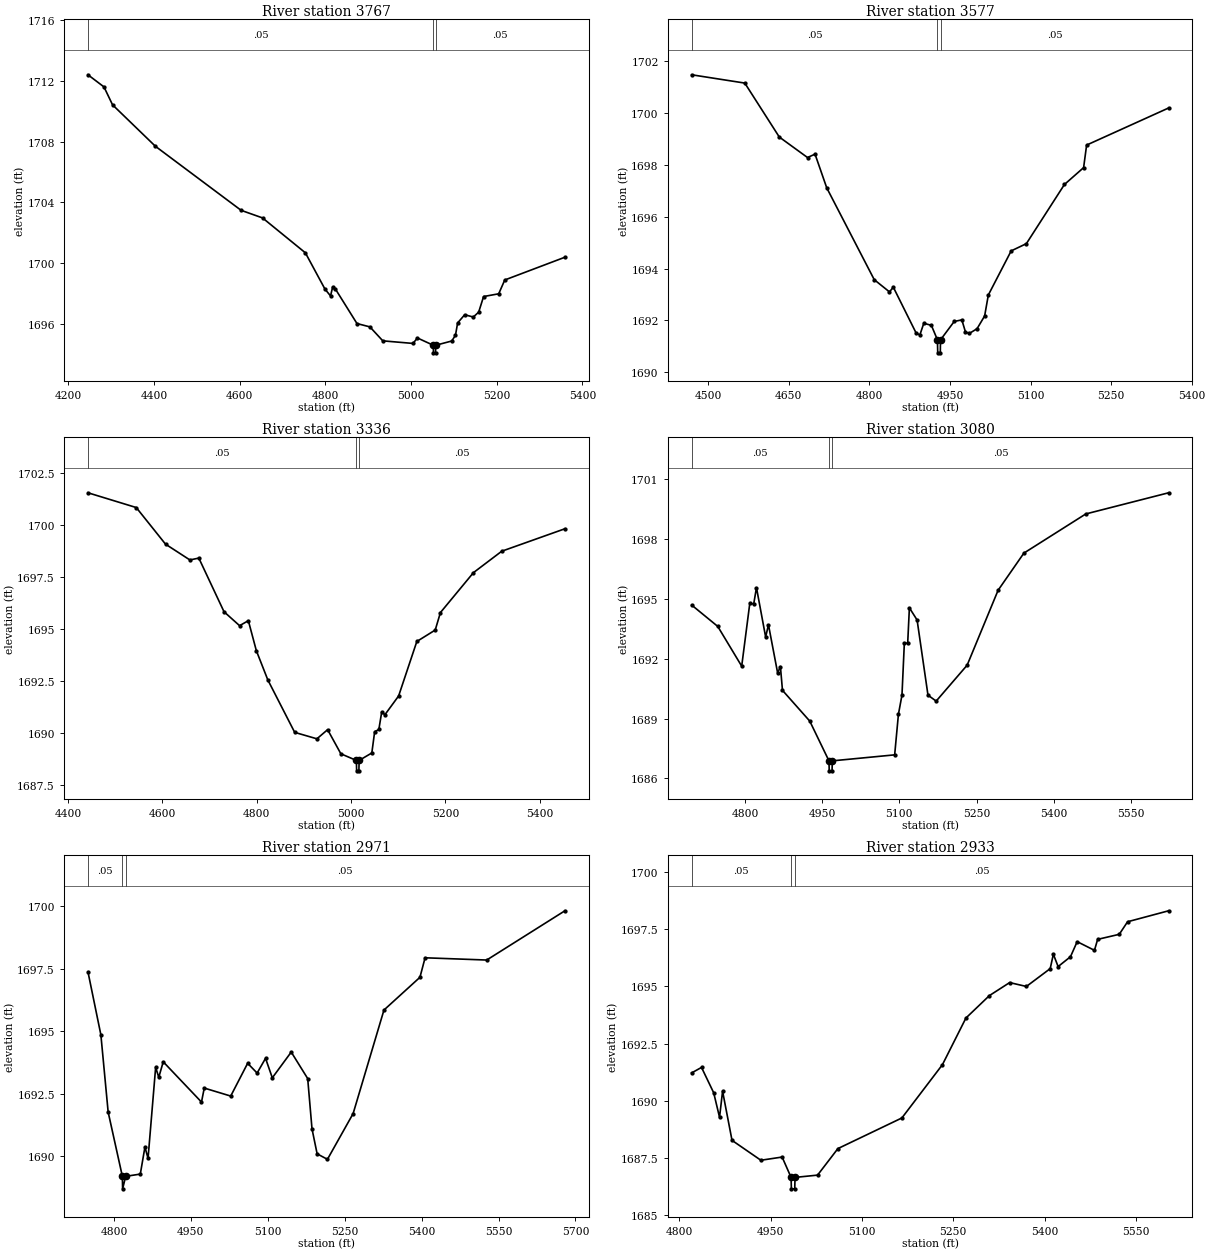
Type RM Length L Ch R = 1,3767,190,190,190
BEGIN DESCRIPTION:
Mapping XS ee513edd
END DESCRIPTION:
XS GIS Cut Line= 4
      1610162.42      6867269.62      1609608.63      6867271.35
      1609256.20      6867307.81      1609110.38      6867451.89
#Sta/Elev= 30
  4245.9 1712.40  4283.3 1711.60  4303.3 1710.42  4403.3 1707.69  4603.3 1703.47
  4653.3 1702.97  4753.3 1700.67  4799.0 1698.28  4812.0 1697.83  4817.1 1698.43
  4823.5 1698.28  4873.7 1696.01  4903.9 1695.79  4934.0 1694.87  5004.4 1694.70
  5014.8 1695.06  5051.8 1694.58  5052.3 1694.08  5057.1 1694.08  5057.5 1694.58
  5094.9 1694.86  5103.6 1695.24  5108.6 1696.05  5125.1 1696.59  5145.2 1696.44
  5157.7 1696.76  5169.2 1697.79  5204.5 1697.97  5218.6 1698.88  5359.0 1700.38
#Mann=3,-1,0
  4245.9    0.05       0  5051.8    0.03       0  5057.5    0.05       0
Bank Sta=5051.8,5057.5
Exp/Cntr=0.3,0.1

Type RM Length L Ch R = 1,3577,241,241,241
BEGIN DESCRIPTION:
Mapping XS 2773b402
END DESCRIPTION:
XS GIS Cut Line= 4
      1609705.88      6866866.83      1609443.70      6866979.69
      1609143.35      6867295.66      1609073.92      6867446.67
#Sta/Elev= 30
  4469.4 1701.47  4568.3 1701.15  4632.5 1699.07  4685.0 1698.28  4699.0 1698.41
  4720.8 1697.11  4809.2 1693.57  4837.5 1693.10  4844.7 1693.28  4887.2 1691.51
  4894.1 1691.44  4901.4 1691.89  4915.5 1691.81  4926.8 1691.25  4927.3 1690.75
  4932.1 1690.75  4932.5 1691.25  4958.0 1691.96  4972.2 1692.02  4979.0 1691.55
  4986.3 1691.50  5000.5 1691.68  5014.6 1692.17  5021.5 1692.98  5064.0 1694.68
  5092.3 1694.96  5163.1 1697.24  5198.8 1697.89  5204.4 1698.76  5357.0 1700.19
#Mann=3,-1,0
  4469.4    0.05       0  4926.8    0.05       0  4932.5    0.05       0
Bank Sta=4926.8,4932.5
Exp/Cntr=0.3,0.1

Type RM Length L Ch R = 1,3336,256,256,256
BEGIN DESCRIPTION:
Mapping XS 7351bd4a
END DESCRIPTION:
XS GIS Cut Line= 4
      1609644.19      6866783.41      1609181.98      6866902.76
      1609071.30      6867063.35      1609064.79      6867401.87
#Sta/Elev= 30
  4442.3 1701.56  4544.7 1700.85  4606.7 1699.09  4658.4 1698.33  4677.3 1698.42
  4730.7 1695.84  4763.7 1695.17  4782.3 1695.41  4799.2 1693.97  4823.6 1692.56
  4880.5 1690.04  4927.6 1689.73  4950.3 1690.17  4978.4 1689.01  5011.3 1688.69
  5011.8 1688.19  5016.6 1688.19  5017.1 1688.69  5044.0 1689.05  5050.0 1690.07
  5058.9 1690.18  5064.9 1691.01  5071.8 1690.89  5100.8 1691.79  5139.4 1694.41
  5178.4 1694.96  5189.4 1695.80  5259.4 1697.72  5319.4 1698.75  5453.3 1699.83
#Mann=3,-1,0
  4442.3    0.05       0  5011.3    0.05       0  5017.1    0.05       0
Bank Sta=5011.3,5017.1
Exp/Cntr=0.3,0.1

Type RM Length L Ch R = 1,3080,109,109,109
BEGIN DESCRIPTION:
Mapping XS b6c0e9b2
END DESCRIPTION:
XS GIS Cut Line= 6
      1609049.73      6866554.74      1608976.79      6866718.84
      1608955.96      6866895.92      1609024.97      6866981.86
      1609040.59      6867204.51      1609043.20      6867438.93
#Sta/Elev= 30
  4696.6 1694.68  4747.3 1693.61  4793.8 1691.62  4809.6 1694.78  4817.1 1694.73
  4822.5 1695.55  4840.3 1693.08  4845.8 1693.69  4863.6 1691.28  4869.0 1691.60
  4873.0 1690.41  4926.0 1688.87  4963.3 1686.88  4963.8 1686.38  4969.3 1686.38
  4969.8 1686.88  5090.9 1687.18  5098.2 1689.21  5105.1 1690.17  5109.7 1692.77
  5116.2 1692.77  5119.5 1694.54  5134.5 1693.93  5155.6 1690.17  5171.5 1689.87
  5231.7 1691.67  5291.8 1695.42  5341.9 1697.28  5462.1 1699.24  5623.0 1700.30
#Mann=3,-1,0
  4696.6    0.05       0  4963.3    0.05       0  4969.8    0.05       0
Bank Sta=4963.3,4969.8
Exp/Cntr=0.3,0.1

Type RM Length L Ch R = 1,2971,38,38,38
BEGIN DESCRIPTION:
Mapping XS bdf97352
END DESCRIPTION:
XS GIS Cut Line= 6
      1608962.46      6866664.18      1608863.51      6866881.60
      1608872.62      6866927.17      1608898.67      6866961.02
      1608993.72      6866966.23      1609026.27      6867470.16
#Sta/Elev= 30
  4749.4 1697.37  4774.6 1694.85  4788.8 1691.76  4816.5 1689.19  4817.0 1688.69
  4823.0 1689.19  4851.5 1689.28  4860.5 1690.36  4866.6 1689.91  4881.4 1693.55
  4887.5 1693.15  4896.2 1693.77  4970.8 1692.16  4976.2 1692.72  5027.8 1692.40
  5060.8 1693.71  5079.3 1693.32  5095.7 1693.91  5108.9 1693.13  5145.8 1694.16
  5177.9 1693.10  5186.3 1691.09  5196.3 1690.09  5216.4 1689.87  5266.5 1691.70
  5326.6 1695.84  5396.8 1697.15  5406.8 1697.93  5527.0 1697.84  5679.5 1699.81
#Mann=3,-1,0
  4749.4    0.05       0  4816.5    0.05       0  4823.0    0.05       0
Bank Sta=4816.5,4823
Exp/Cntr=0.3,0.1

Type RM Length L Ch R = 1,2933,150,150,150
BEGIN DESCRIPTION:
Mapping XS f78dec09
END DESCRIPTION:
XS GIS Cut Line= 5
      1608832.26      6866731.81      1608827.05      6866847.74
      1608838.77      6866964.93      1608955.96      6867362.07
      1608989.74      6867493.30
#Sta/Elev= 30
  4820.4 1691.22  4836.6 1691.46  4856.6 1690.35  4866.2 1689.28  4871.2 1690.42
  4886.7 1688.27  4934.1 1687.40  4969.0 1687.54  4983.7 1686.65  4984.2 1686.15
  4989.7 1686.15  4990.2 1686.65  5027.2 1686.75  5060.6 1687.91  5165.7 1689.25
  5232.3 1691.58  5270.9 1693.62  5309.4 1694.60  5342.7 1695.17  5370.2 1695.00
  5409.3 1695.78  5414.5 1696.41  5422.3 1695.87  5442.6 1696.30  5453.6 1696.96
  5482.0 1696.58  5487.2 1697.06  5522.7 1697.28  5536.4 1697.83  5603.8 1698.31
#Mann=3,-1,0
  4820.4    0.05       0  4983.7    0.05       0  4990.2    0.05       0
Bank Sta=4983.7,4990.2
Exp/Cntr=0.3,0.1

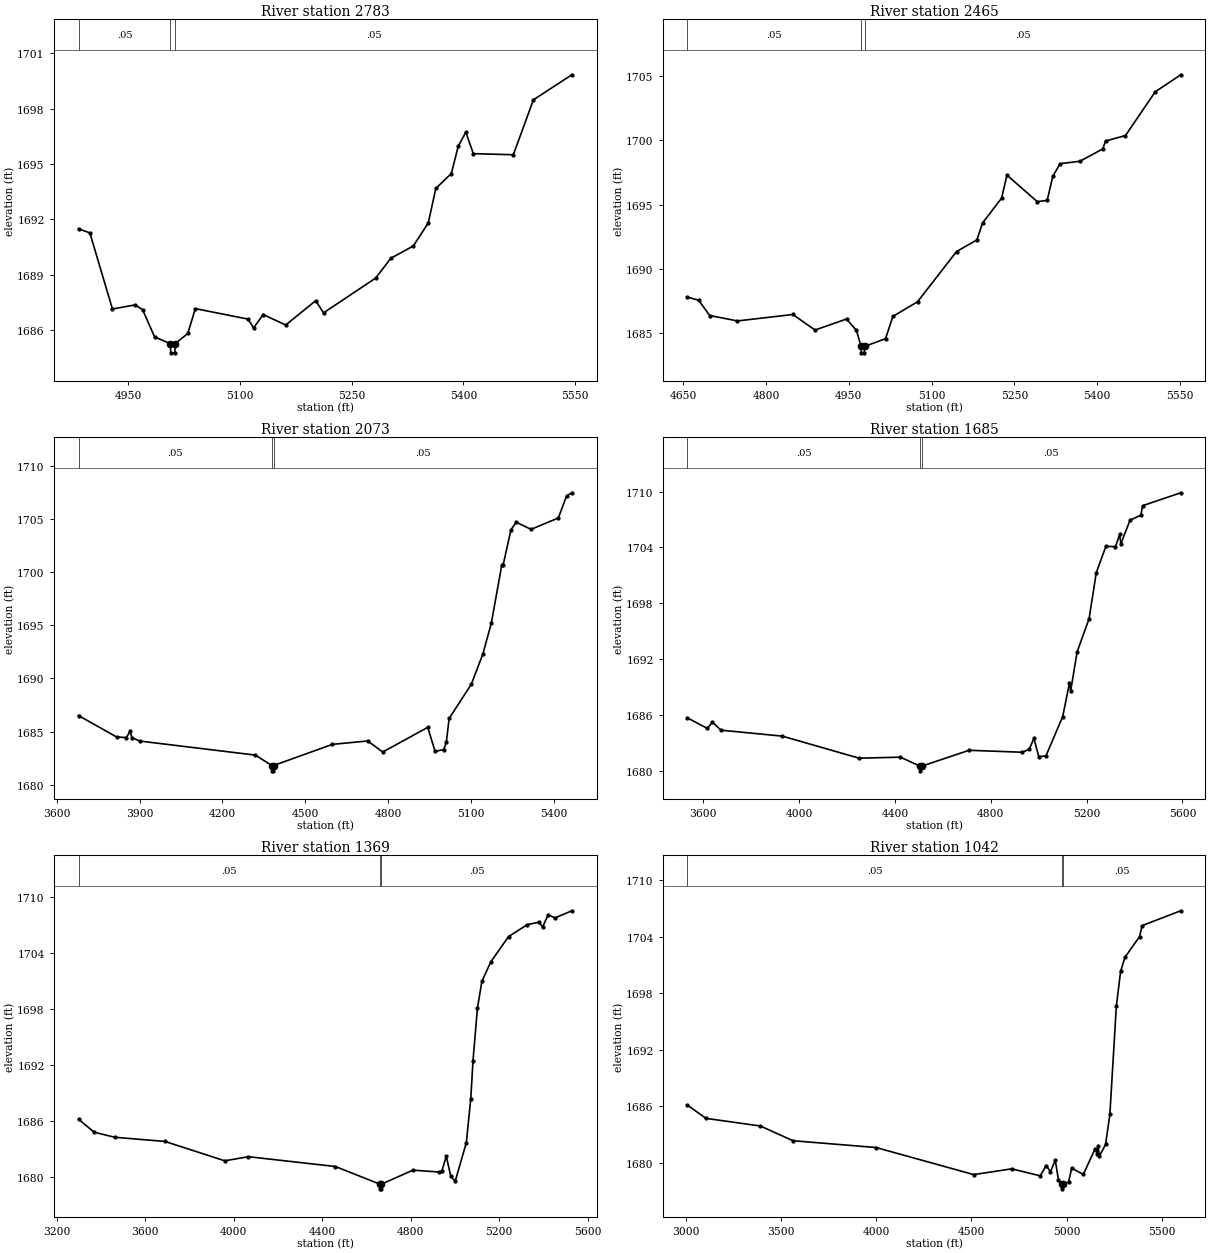
Type RM Length L Ch R = 1,2783,318,318,318
BEGIN DESCRIPTION:
Mapping XS 8c841361
END DESCRIPTION:
XS GIS Cut Line= 3
      1608674.71      6866822.98      1608709.86      6867057.38
      1608759.35      6867479.27
#Sta/Elev= 30
  4883.7 1691.48  4898.9 1691.26  4929.2 1687.13  4959.6 1687.35  4969.7 1687.09
  4985.8 1685.61  5006.9 1685.25  5007.4 1684.75  5012.9 1684.75  5013.4 1685.25
  5030.3 1685.80  5040.4 1687.15  5111.2 1686.58  5118.5 1686.10  5131.4 1686.83
  5161.6 1686.26  5201.9 1687.58  5212.4 1686.92  5282.4 1688.81  5302.6 1689.88
  5332.8 1690.55  5352.9 1691.80  5363.0 1693.67  5383.8 1694.48  5393.2 1695.98
  5403.3 1696.72  5413.3 1695.56  5467.0 1695.50  5493.9 1698.48  5545.5 1699.84
#Mann=3,-1,0
  4883.7    0.05       0  5006.9    0.05       0  5013.4    0.05       0
Bank Sta=5006.9,5013.4
Exp/Cntr=0.3,0.1

Type RM Length L Ch R = 1,2465,392,392,392
BEGIN DESCRIPTION:
Mapping XS 881b1bdb
END DESCRIPTION:
XS GIS Cut Line= 4
      1608502.62      6866837.76      1608480.91      6867074.31
      1608619.80      6867397.66      1608693.59      6867692.82
#Sta/Elev= 30
  4657.8 1687.82  4678.1 1687.58  4698.2 1686.39  4748.4 1685.97  4848.8 1686.47
  4889.0 1685.26  4946.0 1686.12  4964.1 1685.23  4972.3 1683.99  4972.8 1683.49
  4978.3 1683.49  4978.8 1683.99  5016.7 1684.59  5030.0 1686.32  5074.7 1687.46
  5145.3 1691.36  5182.3 1692.27  5192.4 1693.58  5226.9 1695.51  5236.7 1697.30
  5291.6 1695.24  5309.5 1695.34  5319.8 1697.22  5332.9 1698.19  5369.0 1698.38
  5410.2 1699.34  5415.3 1699.95  5451.4 1700.38  5505.3 1703.78  5551.5 1705.10
#Mann=3,-1,0
  4657.8    0.05       0  4972.3    0.05       0  4978.8    0.05       0
Bank Sta=4972.3,4978.8
Exp/Cntr=0.3,0.1

Type RM Length L Ch R = 1,2073,388,388,388
BEGIN DESCRIPTION:
Mapping XS 6cc32227
END DESCRIPTION:
XS GIS Cut Line= 6
      1608504.21      6866113.78      1608184.79      6866481.81
      1608089.85      6866679.34      1608125.01      6867043.92
      1608229.18      6867599.48      1608224.84      6867747.02
#Sta/Elev= 30
  3679.0 1686.51  3816.6 1684.50  3851.7 1684.44  3865.9 1685.03  3872.5 1684.43
  3901.0 1684.11  4319.4 1682.79  4378.5 1681.81  4379.0 1681.31  4384.6 1681.31
  4385.1 1681.81  4597.8 1683.80  4725.7 1684.12  4780.1 1683.08  4942.9 1685.40
  4969.6 1683.14  5000.5 1683.31  5010.3 1683.99  5020.4 1686.24  5100.6 1689.45
  5142.5 1692.30  5173.0 1695.19  5210.8 1700.65  5215.9 1700.69  5244.3 1704.00
  5263.4 1704.70  5317.0 1704.03  5415.6 1705.10  5445.6 1707.18  5464.6 1707.47
#Mann=3,-1,0
  3679.0    0.05       0  4378.5    0.05       0  4385.1    0.05       0
Bank Sta=4378.5,4385.1
Exp/Cntr=0.3,0.1

Type RM Length L Ch R = 1,1685,316,316,316
BEGIN DESCRIPTION:
Mapping XS 3aa437e3
END DESCRIPTION:
XS GIS Cut Line= 6
      1608443.49      6866089.43      1608049.37      6866412.36
      1607817.49      6866712.43      1607775.62      6867119.88
      1607801.66      6867662.41      1607905.14      6867854.29
#Sta/Elev= 30
  3533.5 1685.68  3616.8 1684.55  3637.6 1685.22  3673.8 1684.36  3929.7 1683.72
  4250.3 1681.35  4422.2 1681.46  4505.0 1680.49  4505.5 1679.99  4511.6 1680.49
  4709.3 1682.20  4930.1 1681.99  4960.1 1682.29  4980.1 1683.48  5000.2 1681.52
  5030.2 1681.59  5100.3 1685.83  5128.5 1689.44  5133.5 1688.58  5160.3 1692.77
  5210.4 1696.35  5240.4 1701.29  5280.5 1704.12  5320.5 1704.09  5337.9 1705.40
  5343.0 1704.40  5381.3 1706.93  5426.8 1707.48  5433.6 1708.49  5593.0 1709.88
#Mann=3,-1,0
  3533.5    0.05       0  4505.0    0.05       0  4511.6    0.05       0
Bank Sta=4505,4511.6
Exp/Cntr=0.3,0.1

Type RM Length L Ch R = 1,1369,327,327,327
BEGIN DESCRIPTION:
Mapping XS 5c4c4a40
END DESCRIPTION:
XS GIS Cut Line= 5
      1608453.86      6866056.49      1607585.06      6866764.46
      1607452.27      6867074.31      1607502.18      6867573.44
      1607595.51      6867827.38
#Sta/Elev= 30
  3298.8 1686.19  3370.4 1684.79  3463.0 1684.26  3689.9 1683.81  3959.9 1681.74
  4066.9 1682.18  4459.6 1681.13  4661.2 1679.24  4661.7 1678.74  4667.3 1678.74
  4667.8 1679.24  4810.6 1680.74  4930.5 1680.54  4941.2 1680.66  4961.3 1682.23
  4981.4 1680.09  5001.5 1679.55  5051.8 1683.68  5071.9 1688.40  5081.9 1692.44
  5102.0 1698.09  5122.1 1700.94  5162.3 1703.03  5242.7 1705.74  5327.0 1707.01
  5380.3 1707.28  5396.6 1706.75  5421.7 1708.08  5452.2 1707.73  5528.8 1708.50
#Mann=3,-1,0
  3298.8    0.05       0  4661.2    0.05       0  4667.8    0.05       0
Bank Sta=4661.2,4667.8
Exp/Cntr=0.3,0.1

Type RM Length L Ch R = 1,1042,0,0,0
BEGIN DESCRIPTION:
Elm 02 38 3750.834
END DESCRIPTION:
XS GIS Cut Line= 5
      1608453.85      6866032.19      1607487.28      6866752.67
      1607106.78      6867213.63      1607214.86      6867508.68
      1607419.70      6867932.26
#Sta/Elev= 30
  3009.9 1686.15  3106.8 1684.74  3392.5 1683.93  3563.5 1682.37  3999.3 1681.65
  4511.9 1678.78  4711.2 1679.39  4860.4 1678.65  4892.4 1679.74  4914.4 1679.08
  4939.6 1680.29  4956.3 1678.24  4974.3 1677.77  4974.8 1677.27  4980.9 1677.77
  5009.5 1678.01  5025.8 1679.46  5086.8 1678.80  5148.8 1681.52  5158.3 1681.00
  5163.8 1681.86  5171.1 1680.75  5203.5 1681.97  5226.1 1685.16  5259.9 1696.60
  5282.4 1700.32  5304.9 1701.80  5382.1 1704.01  5395.3 1705.17  5597.9 1706.74
#Mann=3,-1,0
  3009.9    0.05       0  4974.3    0.05       0  4980.9    0.05       0
Bank Sta=4974.3,4980.9
Exp/Cntr=0.3,0.1

Chan Stop Cuts=-1