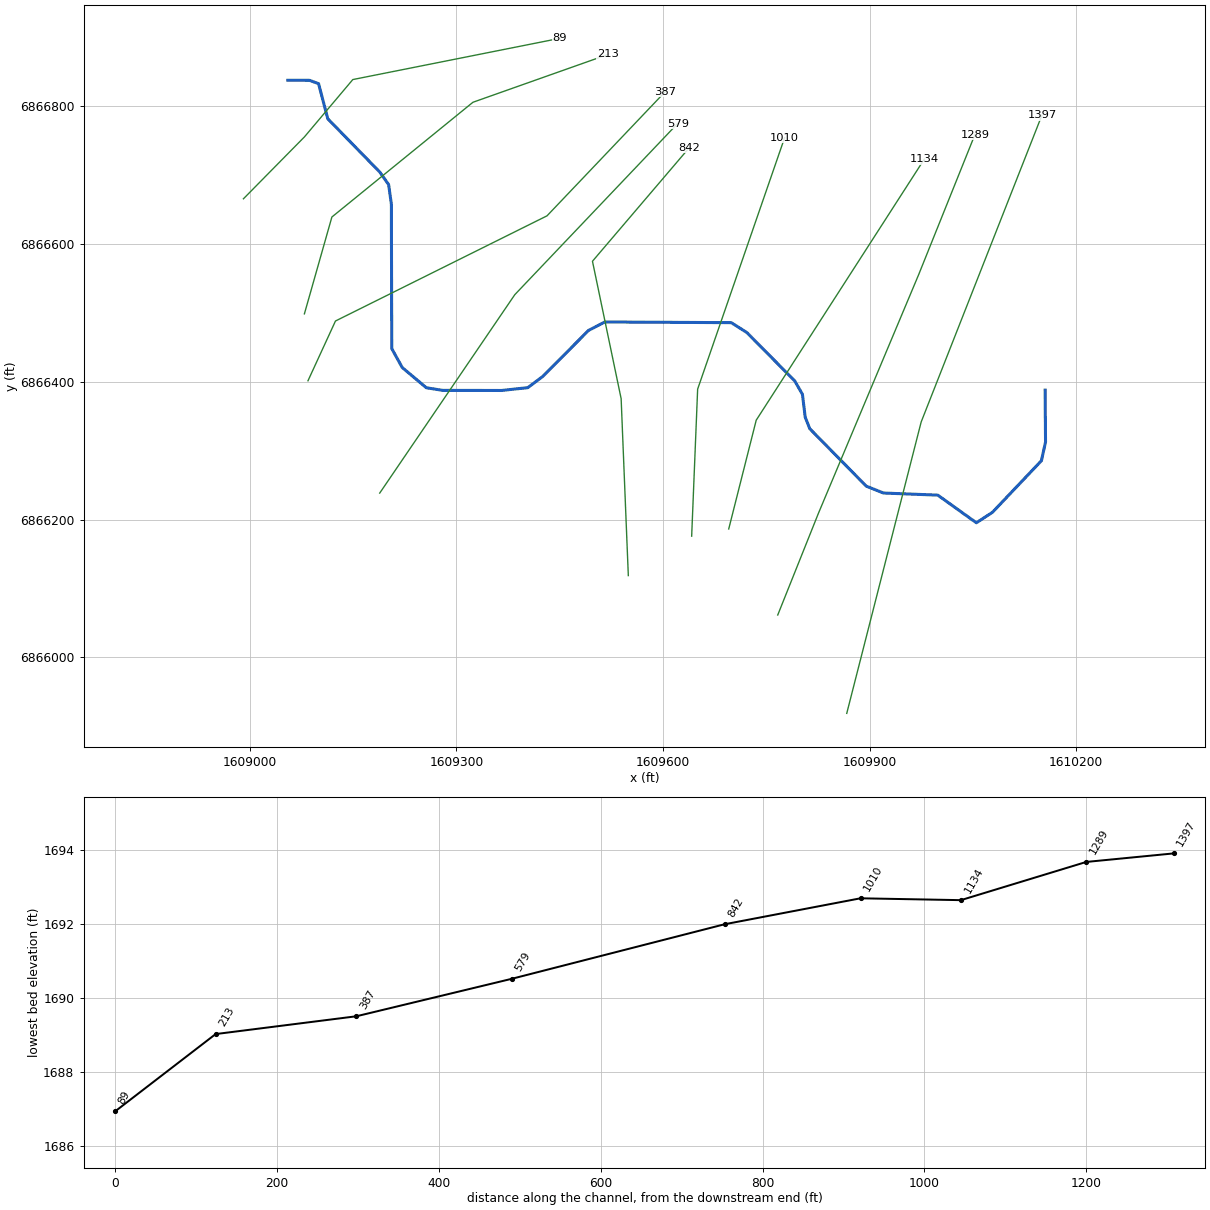
--- Elm 02 39.prj (project) ---

Proj Title=Elm 02 39 Base Level Engineering
Current Plan=p01
Default Exp/Contr=0.3,0.1
English Units
Geom File=g01
Flow File=f01
Plan File=p01
BEGIN DESCRIPTION:
Elm 02 39
END DESCRIPTION:

--- Elm 02 39.p01 (plan) ---

Plan Title=Multiple Run
Short Identifier=Multiple
Geom File=g01
Flow File=f01
Subcritical Flow
K Sum by GR= 0
Std Step Tol= 0.01
Critical Tol= 0.01
Num of Std Step Trials= 20
Max Error Tol= 0.3
Flow Tol Ratio= 0.001
Split Flow NTrial= 30
Split Flow Tol= 0.02
Split Flow Ratio= 0.02
Log Output Level= 0
Friction Slope Method= 1
Unsteady Friction Slope Method= 2
Unsteady Bridges Friction Slope Method= 1
Parabolic Critical Depth
Global Vel Dist=  1 , 1 , 1
Global Log Level= 0
CheckData=True
Encroach Param= -1, 0, 0, 0
BEGIN DESCRIPTION:
Multiple Run
END DESCRIPTION:

--- Elm 02 39.f01 (steady flow) ---

Flow Title=Multiple
Number of Profiles=7
Profile Names=10-year,25-year,50-year,1pct_min,100-year,1pct_plu,500-year
River Rch & RM= Elm 02 39,Reach-1,1397
      83     107     126      92     147     203     204
Boundary for River Rch & Prof#=Elm 02 39,Reach-1,1
Up Type=0
Dn Type=3
Dn Slope=0.001
Boundary for River Rch & Prof#=Elm 02 39,Reach-1,2
Up Type=0
Dn Type=3
Dn Slope=0.001
Boundary for River Rch & Prof#=Elm 02 39,Reach-1,3
Up Type=0
Dn Type=3
Dn Slope=0.001
Boundary for River Rch & Prof#=Elm 02 39,Reach-1,4
Up Type=0
Dn Type=3
Dn Slope=0.001
Boundary for River Rch & Prof#=Elm 02 39,Reach-1,5
Up Type=0
Dn Type=3
Dn Slope=0.001
Boundary for River Rch & Prof#=Elm 02 39,Reach-1,6
Up Type=0
Dn Type=3
Dn Slope=0.001
Boundary for River Rch & Prof#=Elm 02 39,Reach-1,7
Up Type=0
Dn Type=3
Dn Slope=0.001

--- Elm 02 39.g01 (geometry) ---

Geom Title=Existing Conditions

River Reach=Elm 02 39,Reach-1
Reach XY= 30
      1610155.00      6866388.00      1610155.60      6866312.74
      1610149.65      6866285.47      1610078.41      6866210.42
      1610055.11      6866195.31      1609999.11      6866235.44
      1609920.21      6866238.51      1609895.19      6866248.51
      1609813.15      6866331.93      1609806.55      6866348.64
      1609802.47      6866381.96      1609791.38      6866401.24
      1609721.80      6866471.58      1609699.16      6866485.95
      1609515.44      6866486.95      1609491.69      6866474.60
      1609425.14      6866407.65      1609403.53      6866391.54
      1609365.18      6866387.45      1609279.79      6866387.64
      1609256.22      6866391.43      1609221.24      6866420.77
      1609205.98      6866448.26      1609205.43      6866658.18
      1609201.45      6866686.53      1609188.54      6866704.76
      1609113.08      6866782.11      1609099.68      6866833.08
      1609086.54      6866837.93      1609055.00      6866838.00

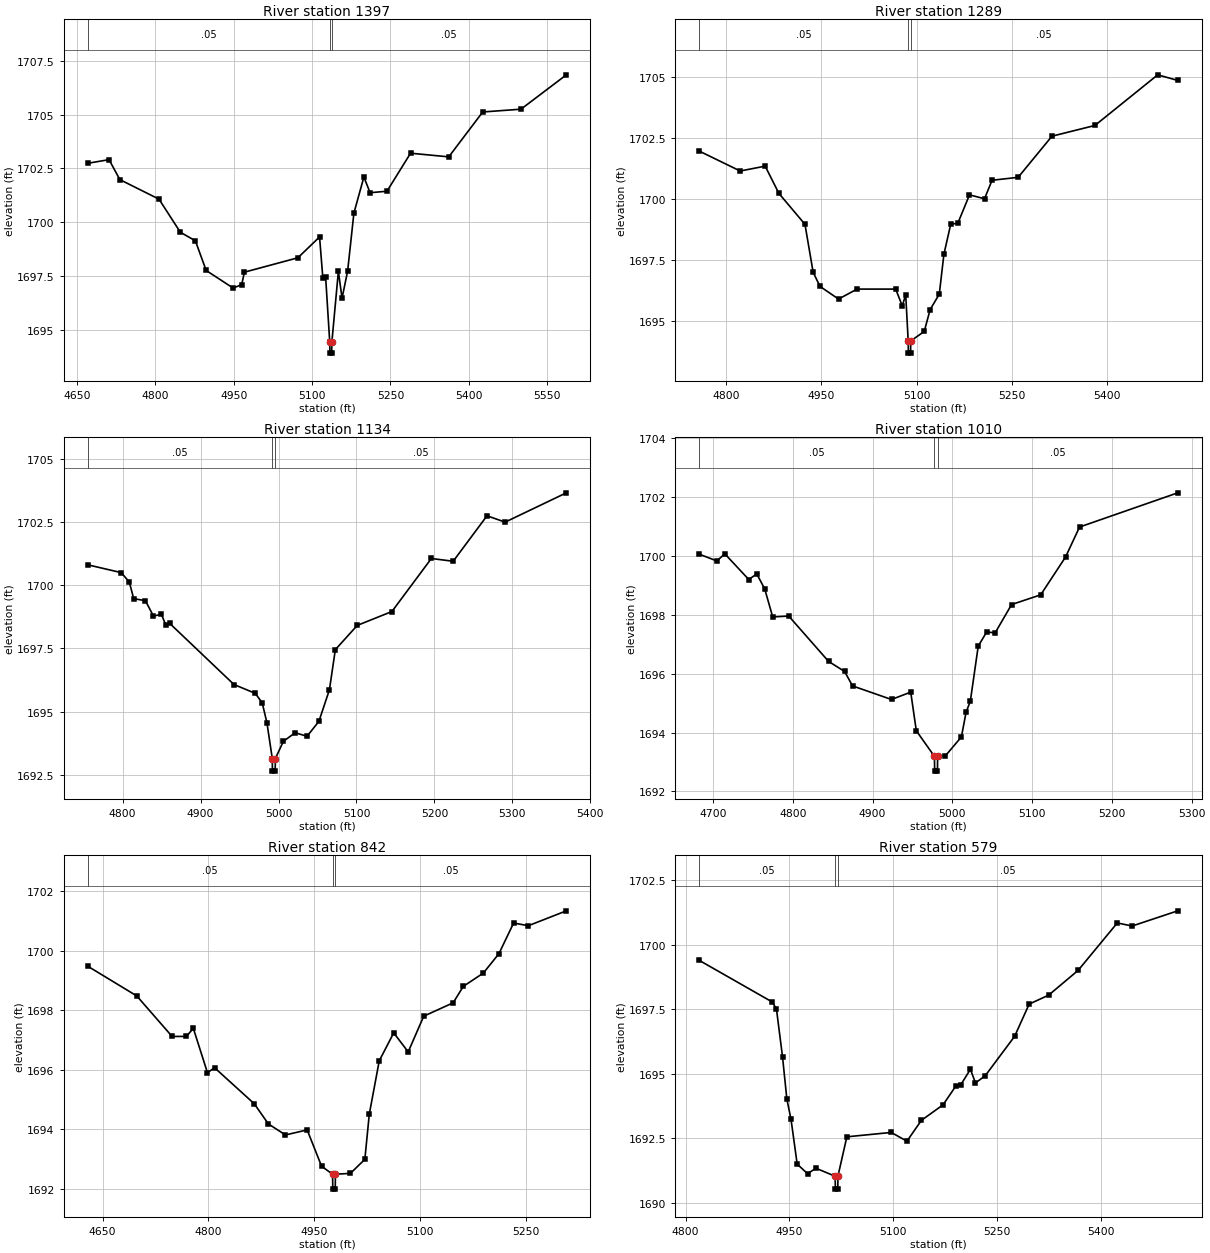
Type RM Length L Ch R = 1,1397,108,108,108
BEGIN DESCRIPTION:
Elm 02 39 2.0
END DESCRIPTION:
XS GIS Cut Line= 3
      1609866.86      6865918.45      1609974.95      6866341.67
      1610150.38      6866787.39
#Sta/Elev= 30
  4670.8 1702.74  4711.6 1702.91  4732.3 1701.98  4807.2 1701.07  4848.0 1699.53
  4876.8 1699.13  4897.4 1697.75  4949.0 1696.93  4965.4 1697.09  4970.6 1697.67
  5072.9 1698.34  5114.4 1699.31  5120.6 1697.42  5126.0 1697.45  5133.9 1694.40
  5134.1 1693.90  5137.6 1693.90  5137.9 1694.40  5150.4 1697.71  5157.4 1696.46
  5168.1 1697.72  5180.1 1700.42  5199.2 1702.10  5211.1 1701.37  5243.4 1701.44
  5288.5 1703.21  5361.6 1703.04  5426.6 1705.13  5499.8 1705.26  5586.6 1706.86
#Mann=3,-1,0
  4670.8    0.05       0  5133.9    0.05       0  5137.9    0.05       0
Bank Sta=5133.9,5137.9
Exp/Cntr=0.3,0.1

Type RM Length L Ch R = 1,1289,155,155,155
BEGIN DESCRIPTION:
Mapping XS b5fb2327
END DESCRIPTION:
XS GIS Cut Line= 4
      1609766.62      6866061.31      1609825.64      6866208.85
      1609971.47      6866556.08      1610053.07      6866759.19
#Sta/Elev= 30
  4757.2 1701.97  4821.9 1701.15  4861.3 1701.35  4882.9 1700.23  4924.0 1698.96
  4936.9 1696.99  4947.7 1696.41  4976.9 1695.89  5006.1 1696.30  5067.0 1696.30
  5077.4 1695.61  5082.8 1696.07  5086.7 1694.17  5087.0 1693.67  5090.5 1693.67
  5090.7 1694.17  5112.0 1694.56  5121.3 1695.46  5135.7 1696.09  5143.0 1697.73
  5153.8 1698.97  5164.9 1699.00  5183.3 1700.17  5207.0 1700.01  5218.9 1700.77
  5260.0 1700.89  5313.3 1702.58  5381.0 1703.02  5480.0 1705.10  5511.6 1704.87
#Mann=3,-1,0
  4757.2    0.05       0  5086.7    0.05       0  5090.7    0.05       0
Bank Sta=5086.7,5090.7
Exp/Cntr=0.3,0.1

Type RM Length L Ch R = 1,1134,124,124,124
BEGIN DESCRIPTION:
Mapping XS 9945fe8f
END DESCRIPTION:
XS GIS Cut Line= 3
      1609695.43      6866186.28      1609735.36      6866344.27
      1609979.58      6866723.59
#Sta/Elev= 30
  4755.2 1700.81  4798.2 1700.50  4808.5 1700.13  4814.2 1699.47  4829.2 1699.39
  4839.5 1698.78  4849.8 1698.85  4855.2 1698.43  4860.4 1698.49  4942.8 1696.07
  4970.2 1695.72  4979.1 1695.34  4985.1 1694.56  4992.0 1693.14  4992.2 1692.64
  4995.7 1692.64  4996.0 1693.14  5006.2 1693.82  5021.4 1694.16  5036.6 1694.02
  5051.8 1694.61  5065.3 1695.86  5072.9 1697.45  5101.0 1698.41  5145.5 1698.96
  5196.1 1701.06  5224.1 1700.95  5267.5 1702.75  5290.8 1702.50  5369.3 1703.66
#Mann=3,-1,0
  4755.2    0.05       0  4992.0    0.05       0  4996.0    0.05       0
Bank Sta=4992,4996
Exp/Cntr=0.3,0.1

Type RM Length L Ch R = 1,1010,168,168,168
BEGIN DESCRIPTION:
Mapping XS 195dfdbd
END DESCRIPTION:
XS GIS Cut Line= 3
      1609641.61      6866175.84      1609650.29      6866389.41
      1609776.55      6866754.34
#Sta/Elev= 30
  4682.7 1700.05  4704.9 1699.82  4714.9 1700.06  4744.9 1699.19  4754.9 1699.38
  4764.9 1698.87  4774.9 1697.92  4795.0 1697.95  4845.0 1696.41  4865.0 1696.07
  4875.0 1695.58  4923.8 1695.12  4947.9 1695.37  4954.9 1694.06  4977.6 1693.19
  4977.9 1692.69  4981.4 1692.69  4981.6 1693.19  4991.4 1693.21  5011.4 1693.85
  5017.3 1694.69  5022.6 1695.06  5032.5 1696.93  5043.1 1697.41  5053.7 1697.38
  5074.3 1698.34  5110.8 1698.67  5141.9 1699.95  5159.5 1700.97  5282.6 1702.13
#Mann=3,-1,0
  4682.7    0.05       0  4977.6    0.05       0  4981.6    0.05       0
Bank Sta=4977.6,4981.6
Exp/Cntr=0.3,0.1

Type RM Length L Ch R = 1,842,263,263,263
BEGIN DESCRIPTION:
Mapping XS e5af6286
END DESCRIPTION:
XS GIS Cut Line= 4
      1609549.60      6866118.56      1609539.18      6866375.52
      1609497.52      6866575.17      1609638.16      6866740.13
#Sta/Elev= 30
  4629.0 1699.48  4698.5 1698.48  4748.5 1697.12  4768.6 1697.12  4778.6 1697.39
  4798.6 1695.90  4808.6 1696.07  4864.8 1694.86  4884.9 1694.18  4909.1 1693.81
  4939.8 1693.98  4960.2 1692.76  4975.8 1692.49  4976.1 1691.99  4979.6 1691.99
  4979.8 1692.49  5001.1 1692.52  5021.5 1692.99  5027.8 1694.51  5041.9 1696.30
  5062.4 1697.24  5082.9 1696.60  5104.9 1697.80  5146.6 1698.25  5160.9 1698.80
  5189.4 1699.25  5211.4 1699.90  5232.2 1700.93  5253.1 1700.84  5306.9 1701.34
#Mann=3,-1,0
  4629.0    0.05       0  4975.8    0.05       0  4979.8    0.05       0
Bank Sta=4975.8,4979.8
Exp/Cntr=0.3,0.1

Type RM Length L Ch R = 1,579,192,192,192
BEGIN DESCRIPTION:
Mapping XS 925a76e4
END DESCRIPTION:
XS GIS Cut Line= 3
      1609188.51      6866238.41      1609384.67      6866526.56
      1609621.24      6866775.22
#Sta/Elev= 30
  4819.5 1699.40  4925.3 1697.78  4931.3 1697.50  4940.0 1695.66  4946.3 1694.01
  4952.3 1693.23  4961.2 1691.49  4976.2 1691.12  4988.4 1691.33  5016.1 1691.02
  5016.4 1690.52  5019.9 1690.52  5020.1 1691.02  5033.0 1692.55  5097.2 1692.72
  5119.8 1692.38  5140.8 1693.19  5172.0 1693.79  5190.5 1694.52  5197.7 1694.57
  5211.6 1695.17  5218.9 1694.64  5233.0 1694.92  5275.5 1696.45  5296.5 1697.70
  5324.8 1698.05  5367.3 1699.01  5423.9 1700.85  5445.3 1700.73  5511.3 1701.32
#Mann=3,-1,0
  4819.5    0.05       0  5016.1   0.035       0  5020.1    0.05       0
Bank Sta=5016.1,5020.1
Exp/Cntr=0.3,0.1

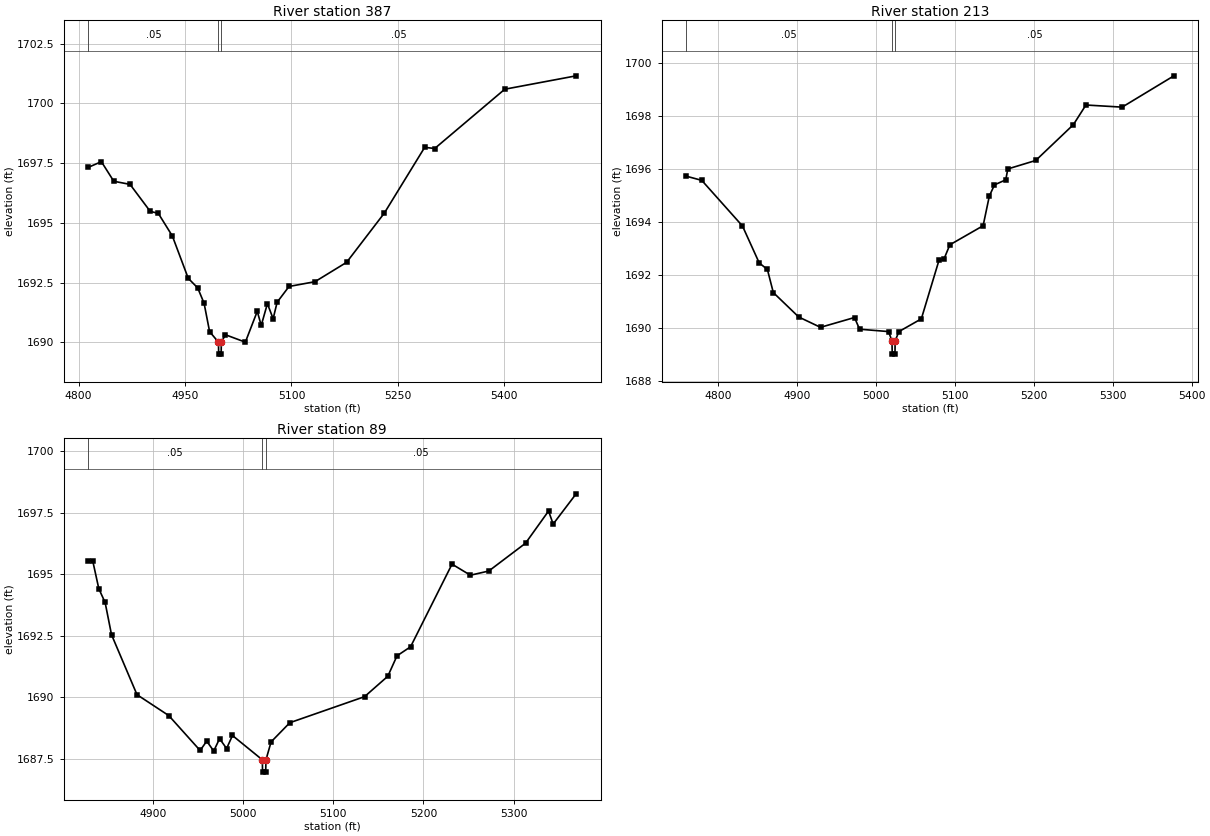
Type RM Length L Ch R = 1,387,174,174,174
BEGIN DESCRIPTION:
Mapping XS d6104f1b
END DESCRIPTION:
XS GIS Cut Line= 4
      1609084.31      6866401.55      1609124.25      6866488.37
      1609431.54      6866641.15      1609603.40      6866821.68
#Sta/Elev= 30
  4813.4 1697.32  4832.0 1697.56  4849.5 1696.74  4872.4 1696.61  4900.9 1695.48
  4912.2 1695.40  4932.1 1694.45  4954.5 1692.68  4967.8 1692.28  4976.8 1691.64
  4984.6 1690.45  4997.1 1690.01  4997.4 1689.51  5000.9 1689.51  5001.1 1690.01
  5007.0 1690.32  5035.0 1690.01  5051.8 1691.30  5057.4 1690.71  5066.1 1691.62
  5074.2 1690.99  5079.8 1691.68  5096.6 1692.34  5133.2 1692.54  5177.8 1693.35
  5231.0 1695.41  5287.9 1698.16  5302.0 1698.11  5400.8 1700.59  5501.4 1701.15
#Mann=3,-1,0
  4813.4    0.05       0  4997.1   0.035       0  5001.1    0.05       0
Bank Sta=4997.1,5001.1
Exp/Cntr=0.3,0.1

Type RM Length L Ch R = 1,213,124,124,124
BEGIN DESCRIPTION:
Mapping XS 30b401e0
END DESCRIPTION:
XS GIS Cut Line= 4
      1609079.11      6866498.76      1609119.04      6866639.41
      1609323.91      6866806.08      1609520.08      6866875.52
#Sta/Elev= 30
  4759.1 1695.74  4779.1 1695.58  4830.7 1693.86  4851.9 1692.47  4862.3 1692.22
  4869.8 1691.35  4902.0 1690.43  4929.6 1690.04  4972.7 1690.41  4979.1 1689.97
  5015.8 1689.88  5020.2 1689.53  5020.5 1689.03  5024.0 1689.03  5024.2 1689.53
  5029.0 1689.88  5057.4 1690.36  5079.7 1692.56  5086.2 1692.62  5093.5 1693.15
  5135.7 1693.87  5143.6 1694.99  5150.1 1695.41  5164.4 1695.60  5167.0 1696.01
  5202.4 1696.33  5250.1 1697.68  5266.0 1698.42  5311.9 1698.34  5377.5 1699.52
#Mann=3,-1,0
  4759.1    0.05       0  5020.2    0.05       0  5024.2    0.05       0
Bank Sta=5020.2,5024.2
Exp/Cntr=0.3,0.1

Type RM Length L Ch R = 1,89,0,0,0
BEGIN DESCRIPTION:
Elm 02 39 1.0
END DESCRIPTION:
XS GIS Cut Line= 4
      1608990.54      6866665.86      1609079.11      6866755.73
      1609149.43      6866839.06      1609450.11      6866898.94
#Sta/Elev= 30
  4827.7 1695.55  4832.7 1695.55  4839.5 1694.41  4846.5 1693.85  4853.6 1692.54
  4881.9 1690.10  4917.2 1689.25  4952.0 1687.83  4959.3 1688.21  4967.1 1687.81
  4973.6 1688.31  4981.4 1687.91  4987.9 1688.44  5021.1 1687.45  5021.3 1686.95
  5024.8 1686.95  5025.1 1687.45  5030.8 1688.18  5051.6 1688.96  5134.6 1690.02
  5160.4 1690.85  5170.6 1691.68  5185.7 1692.05  5231.7 1695.41  5252.1 1694.96
  5272.5 1695.13  5313.3 1696.26  5338.9 1697.57  5344.0 1697.04  5369.5 1698.27
#Mann=3,-1,0
  4827.7    0.05       0  5021.1    0.05       0  5025.1    0.05       0
Bank Sta=5021.1,5025.1
Exp/Cntr=0.3,0.1

Chan Stop Cuts=-1