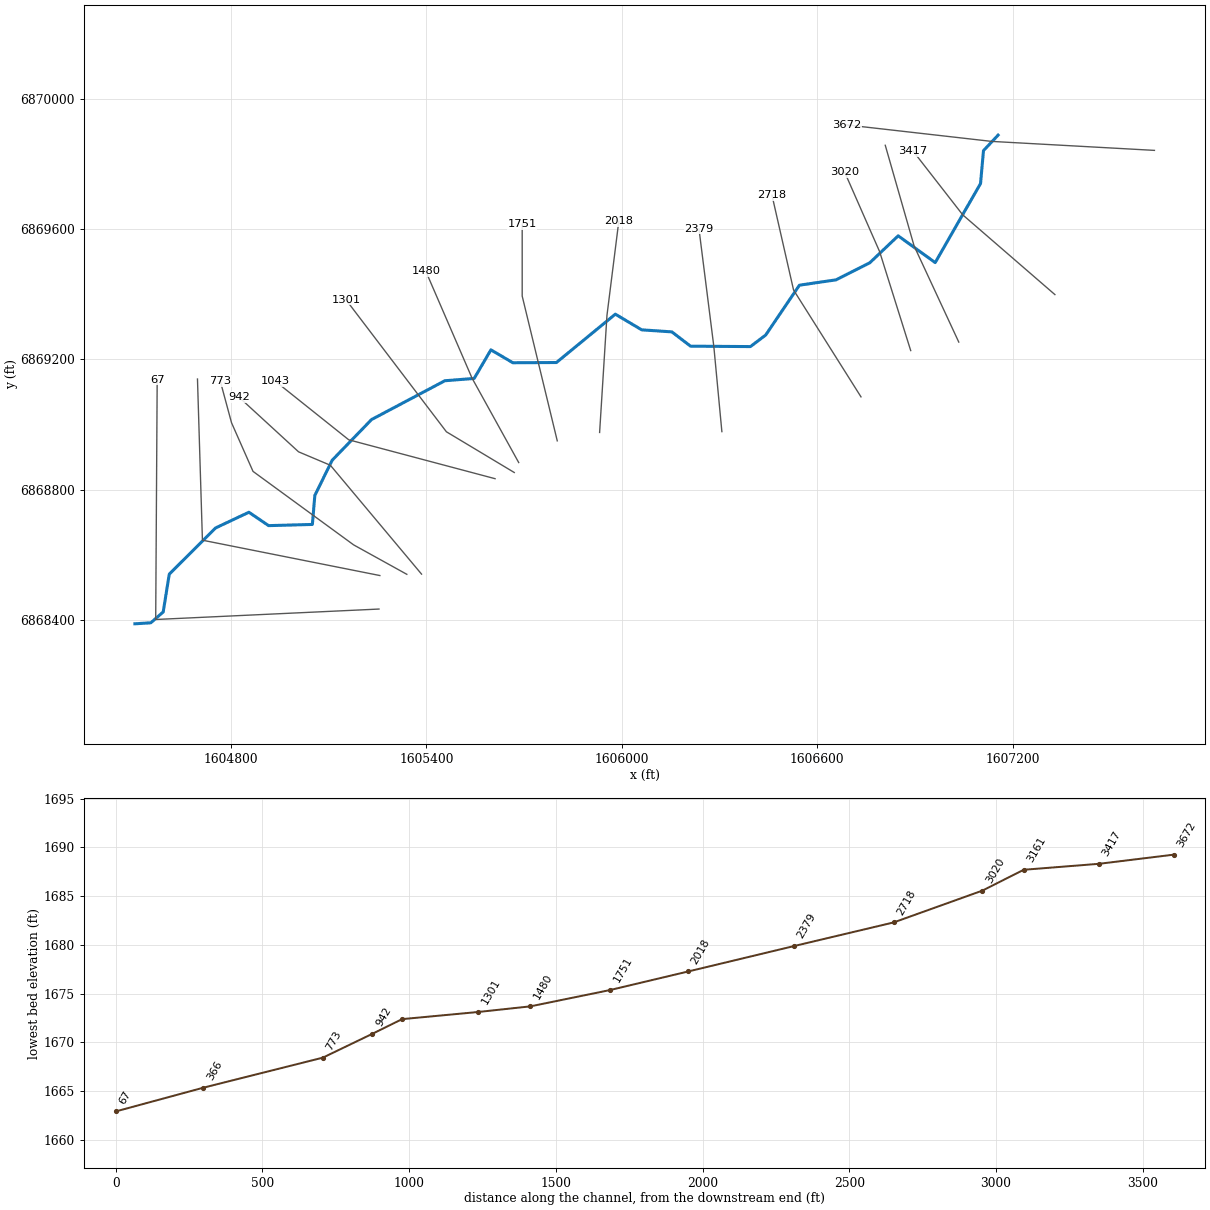
--- Elm 02 40.prj (project) ---

Proj Title=Elm 02 40 Base Level Engineering
Current Plan=p01
Default Exp/Contr=0.3,0.1
English Units
Geom File=g01
Flow File=f01
Plan File=p01
BEGIN DESCRIPTION:
Elm 02 40
END DESCRIPTION:

--- Elm 02 40.p01 (plan) ---

Plan Title=Multiple Run
Short Identifier=Multiple
Geom File=g01
Flow File=f01
Subcritical Flow
K Sum by GR= 0
Std Step Tol= 0.01
Critical Tol= 0.01
Num of Std Step Trials= 20
Max Error Tol= 0.3
Flow Tol Ratio= 0.001
Split Flow NTrial= 30
Split Flow Tol= 0.02
Split Flow Ratio= 0.02
Log Output Level= 0
Friction Slope Method= 1
Unsteady Friction Slope Method= 2
Unsteady Bridges Friction Slope Method= 1
Parabolic Critical Depth
Global Vel Dist=  1 , 1 , 1
Global Log Level= 0
CheckData=True
Encroach Param= -1, 0, 0, 0
BEGIN DESCRIPTION:
Multiple Run
END DESCRIPTION:

--- Elm 02 40.f01 (steady flow) ---

Flow Title=Multiple
Number of Profiles=7
Profile Names=10-year,25-year,50-year,1pct_min,100-year,1pct_plu,500-year
River Rch & RM= Elm 02 40,Reach-1,3672
      96     125     148     108     173     239     242
Boundary for River Rch & Prof#=Elm 02 40,Reach-1,1
Up Type=0
Dn Type=3
Dn Slope=0.001
Boundary for River Rch & Prof#=Elm 02 40,Reach-1,2
Up Type=0
Dn Type=3
Dn Slope=0.001
Boundary for River Rch & Prof#=Elm 02 40,Reach-1,3
Up Type=0
Dn Type=3
Dn Slope=0.001
Boundary for River Rch & Prof#=Elm 02 40,Reach-1,4
Up Type=0
Dn Type=3
Dn Slope=0.001
Boundary for River Rch & Prof#=Elm 02 40,Reach-1,5
Up Type=0
Dn Type=3
Dn Slope=0.001
Boundary for River Rch & Prof#=Elm 02 40,Reach-1,6
Up Type=0
Dn Type=3
Dn Slope=0.001
Boundary for River Rch & Prof#=Elm 02 40,Reach-1,7
Up Type=0
Dn Type=3
Dn Slope=0.001

--- Elm 02 40.g01 (geometry) ---

Geom Title=Existing Conditions

River Reach=Elm 02 40,Reach-1
Reach XY= 30
      1607155.00      6869888.00      1607110.22      6869840.55
      1607101.20      6869739.57      1606961.95      6869496.85
      1606848.34      6869579.01      1606761.06      6869496.18
      1606657.32      6869443.77      1606545.19      6869427.49
      1606441.54      6869274.37      1606394.72      6869238.98
      1606210.94      6869240.26      1606153.40      6869284.14
      1606060.97      6869290.38      1605979.96      6869338.50
      1605799.14      6869190.05      1605665.43      6869189.38
      1605598.00      6869228.94      1605546.66      6869141.21
      1605456.66      6869134.14      1605231.53      6869014.99
      1605110.83      6868890.30      1605057.37      6868781.94
      1605049.92      6868693.02      1604915.46      6868689.36
      1604854.99      6868730.47      1604752.71      6868682.19
      1604610.52      6868540.43      1604591.88      6868424.35
      1604554.01      6868391.12      1604505.00      6868388.00

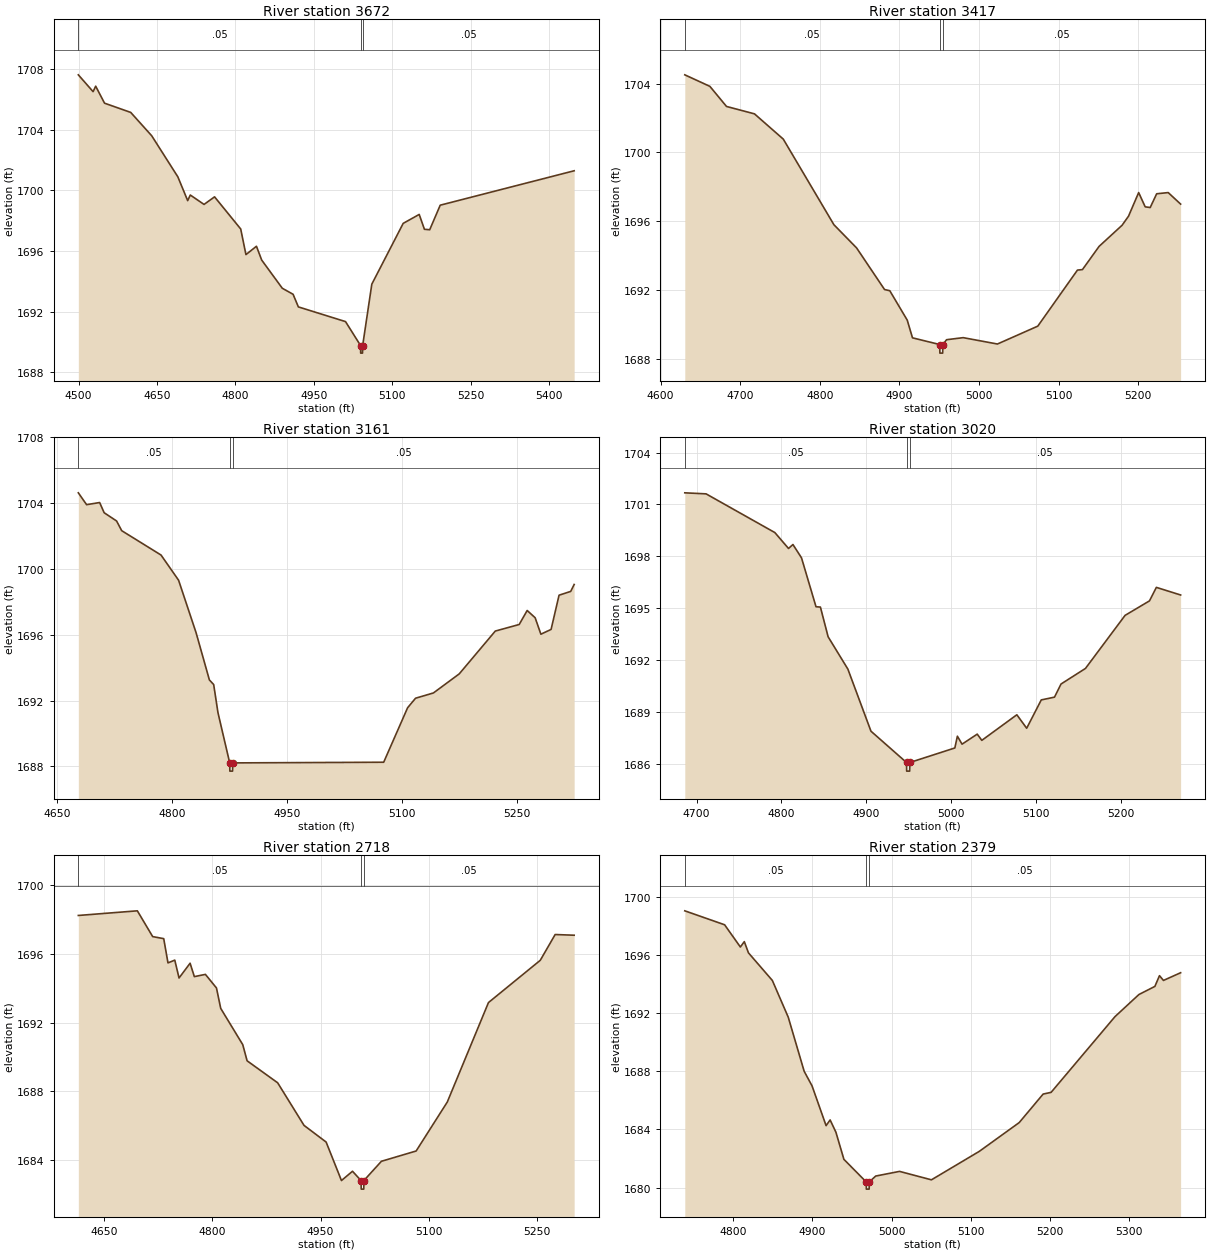
Type RM Length L Ch R = 1,3672,255,255,255
BEGIN DESCRIPTION:
Elm 02 40 3353.443
END DESCRIPTION:
XS GIS Cut Line= 3
      1607635.06      6869841.28      1607135.32      6869868.85
      1606690.58      6869919.41
#Sta/Elev= 30
  4499.5 1707.62  4527.7 1706.51  4532.7 1706.87  4549.6 1705.75  4599.7 1705.14
  4639.8 1703.60  4689.8 1700.89  4708.6 1699.32  4713.6 1699.69  4739.9 1699.07
  4760.0 1699.57  4810.0 1697.45  4820.0 1695.76  4840.1 1696.31  4850.1 1695.40
  4889.5 1693.54  4910.2 1693.14  4920.2 1692.31  5010.4 1691.34  5039.2 1689.76
  5039.4 1689.26  5042.9 1689.26  5043.2 1689.76  5060.7 1693.81  5120.7 1697.82
  5151.3 1698.41  5161.3 1697.43  5171.4 1697.40  5191.5 1699.02  5447.6 1701.29
#Mann=3,-1,0
  4499.5    0.05       0  5039.2    0.03       0  5043.2    0.05       0
Bank Sta=5039.2,5043.2
Exp/Cntr=0.3,0.1

Type RM Length L Ch R = 1,3417,256,256,256
BEGIN DESCRIPTION:
Elm 02 40 3417.45
END DESCRIPTION:
XS GIS Cut Line= 3
      1607329.48      6869398.60      1607046.53      6869643.36
      1606893.74      6869839.56
#Sta/Elev= 30
  4630.4 1704.51  4661.9 1703.84  4682.8 1702.67  4717.9 1702.24  4754.1 1700.77
  4817.7 1695.79  4846.2 1694.44  4881.3 1692.02  4887.9 1691.95  4909.8 1690.24
  4916.4 1689.21  4950.6 1688.82  4950.8 1688.32  4954.3 1688.32  4954.6 1688.82
  4959.2 1689.10  4980.1 1689.22  5023.1 1688.85  5073.8 1689.89  5123.6 1693.15
  5129.9 1693.18  5150.8 1694.53  5179.7 1695.76  5187.8 1696.29  5200.5 1697.66
  5208.7 1696.83  5215.0 1696.79  5223.1 1697.59  5237.6 1697.66  5253.2 1696.99
#Mann=3,-1,0
  4630.4    0.05       0  4950.6    0.03       0  4954.6    0.05       0
Bank Sta=4950.6,4954.6
Exp/Cntr=0.3,0.1

Type RM Length L Ch R = 1,3161,141,141,141
BEGIN DESCRIPTION:
Elm 02 40 3160.6
END DESCRIPTION:
XS GIS Cut Line= 3
      1607034.36      6869252.77      1606897.22      6869547.88
      1606808.67      6869856.93
#Sta/Elev= 30
  4678.2 1704.62  4689.0 1703.90  4706.0 1704.03  4711.9 1703.41  4728.1 1702.91
  4734.8 1702.32  4786.1 1700.84  4809.0 1699.31  4831.9 1696.11  4849.2 1693.25
  4854.8 1692.97  4860.4 1691.26  4875.7 1688.21  4875.9 1687.71  4879.4 1687.71
  4879.7 1688.21  5076.6 1688.25  5107.8 1691.56  5118.2 1692.14  5141.5 1692.46
  5175.2 1693.62  5222.2 1696.22  5253.4 1696.62  5263.8 1697.47  5274.2 1697.03
  5281.7 1696.03  5295.0 1696.32  5305.4 1698.40  5320.6 1698.63  5325.1 1699.05
#Mann=3,-1,0
  4678.2    0.05       0  4875.7    0.05       0  4879.7    0.05       0
Bank Sta=4875.7,4879.7
Exp/Cntr=0.3,0.1

Type RM Length L Ch R = 1,3020,302,302,302
BEGIN DESCRIPTION:
Elm 02 40 3019.52
END DESCRIPTION:
XS GIS Cut Line= 3
      1606886.79      6869226.73      1606791.32      6869530.52
      1606684.18      6869774.16
#Sta/Elev= 30
  4686.1 1701.67  4711.2 1701.61  4792.3 1699.37  4808.4 1698.45  4813.6 1698.68
  4823.7 1697.91  4840.8 1695.08  4846.0 1695.06  4855.1 1693.34  4878.4 1691.47
  4905.6 1687.88  4947.5 1686.07  4947.7 1685.57  4951.2 1685.57  4951.5 1686.07
  5004.5 1686.91  5007.5 1687.59  5013.0 1687.13  5030.9 1687.71  5036.3 1687.35
  5077.6 1688.83  5089.2 1688.05  5106.4 1689.69  5122.0 1689.85  5129.7 1690.61
  5158.5 1691.51  5205.2 1694.58  5234.0 1695.42  5242.1 1696.20  5270.7 1695.76
#Mann=3,-1,0
  4686.1    0.05       0  4947.5    0.05       0  4951.5    0.05       0
Bank Sta=4947.5,4951.5
Exp/Cntr=0.3,0.1

Type RM Length L Ch R = 1,2718,339,339,339
BEGIN DESCRIPTION:
Elm 02 40 2717.65
END DESCRIPTION:
XS GIS Cut Line= 3
      1606734.13      6869084.68      1606527.11      6869412.78
      1606460.88      6869703.68
#Sta/Elev= 30
  4614.7 1698.24  4696.4 1698.51  4717.6 1697.01  4732.9 1696.89  4738.8 1695.48
  4748.2 1695.64  4754.1 1694.60  4769.4 1695.46  4775.3 1694.68  4790.6 1694.81
  4805.9 1694.02  4811.8 1692.83  4842.3 1690.72  4848.3 1689.78  4890.6 1688.50
  4927.1 1686.02  4957.7 1685.05  4978.9 1682.81  4994.2 1683.35  5006.0 1682.81
  5006.3 1682.31  5009.8 1682.31  5010.0 1682.81  5034.2 1683.93  5082.3 1684.53
  5125.4 1687.38  5182.4 1693.17  5254.1 1695.63  5274.7 1697.13  5301.0 1697.09
#Mann=3,-1,0
  4614.7    0.05       0  5006.0    0.03       0  5010.0    0.05       0
Bank Sta=5006,5010
Exp/Cntr=0.3,0.1

Type RM Length L Ch R = 1,2379,361,361,361
BEGIN DESCRIPTION:
Elm 02 40 2378.56
END DESCRIPTION:
XS GIS Cut Line= 3
      1606307.06      6868977.92      1606282.32      6869239.60
      1606236.75      6869600.28
#Sta/Elev= 30
  4738.8 1699.04  4789.1 1698.08  4809.0 1696.55  4814.0 1696.92  4819.2 1696.15
  4849.4 1694.25  4869.5 1691.72  4889.6 1688.00  4899.6 1686.99  4917.3 1684.26
  4922.4 1684.65  4929.7 1683.81  4939.8 1681.94  4967.9 1680.39  4968.2 1679.89
  4971.7 1679.89  4971.9 1680.39  4980.0 1680.79  5010.1 1681.11  5050.4 1680.53
  5110.9 1682.49  5161.3 1684.47  5191.5 1686.43  5201.6 1686.55  5282.3 1691.76
  5312.5 1693.28  5332.7 1693.84  5338.5 1694.58  5343.5 1694.25  5365.2 1694.78
#Mann=3,-1,0
  4738.8    0.05       0  4967.9    0.03       0  4971.9    0.05       0
Bank Sta=4967.9,4971.9
Exp/Cntr=0.3,0.1

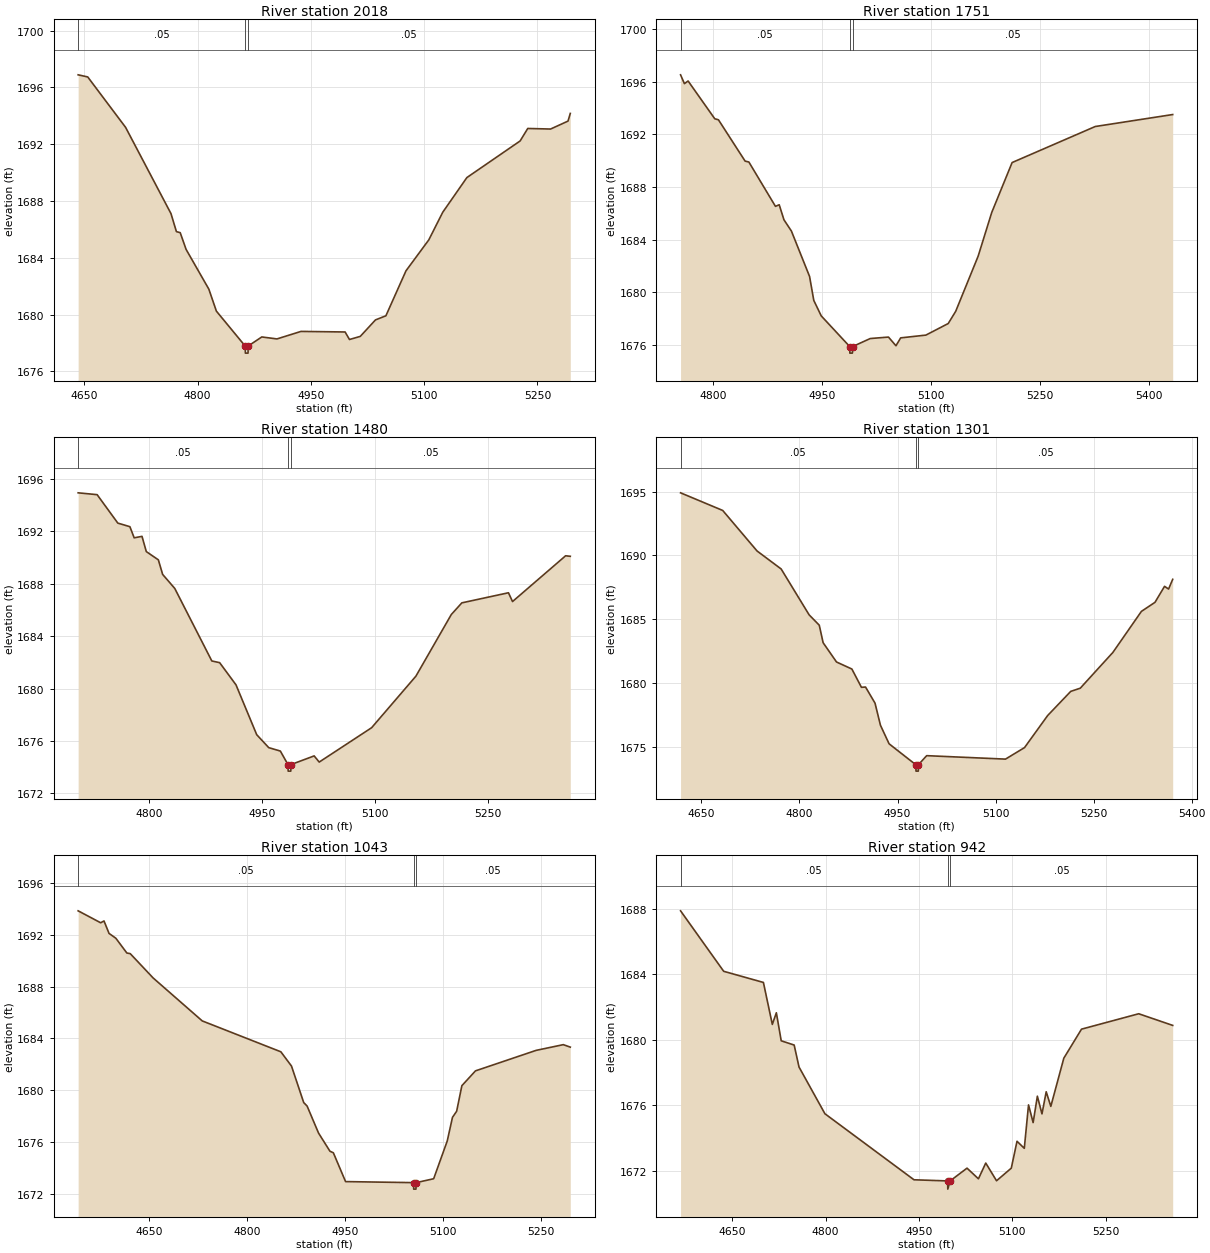
Type RM Length L Ch R = 1,2018,267,267,267
BEGIN DESCRIPTION:
Elm 02 40 2017.98
END DESCRIPTION:
XS GIS Cut Line= 3
      1605931.71      6868975.33      1605954.28      6869334.74
      1605990.64      6869623.85
#Sta/Elev= 30
  4642.0 1696.89  4654.7 1696.74  4704.8 1693.19  4764.9 1687.11  4772.1 1685.84
  4777.1 1685.77  4784.9 1684.59  4815.0 1681.79  4825.0 1680.24  4863.1 1677.78
  4863.4 1677.28  4866.9 1677.28  4867.1 1677.78  4885.1 1678.42  4905.2 1678.28
  4937.0 1678.81  4995.4 1678.77  5001.2 1678.24  5015.5 1678.46  5035.6 1679.62
  5049.4 1679.91  5076.0 1683.08  5106.2 1685.26  5124.7 1687.21  5156.6 1689.65
  5227.1 1692.23  5237.2 1693.11  5267.4 1693.07  5290.5 1693.63  5293.5 1694.17
#Mann=3,-1,0
  4642.0    0.05       0  4863.1    0.05       0  4867.1    0.05       0
Bank Sta=4863.1,4867.1
Exp/Cntr=0.3,0.1

Type RM Length L Ch R = 1,1751,271,271,271
BEGIN DESCRIPTION:
Mapping XS c3d13f12
END DESCRIPTION:
XS GIS Cut Line= 3
      1605801.67      6868949.64      1605694.02      6869394.10
      1605694.02      6869614.69
#Sta/Elev= 30
  4754.8 1696.53  4760.1 1695.86  4765.2 1696.06  4801.9 1693.19  4807.0 1693.11
  4843.7 1689.97  4848.9 1689.90  4885.5 1686.53  4890.7 1686.65  4897.2 1685.51
  4907.5 1684.65  4932.5 1681.20  4938.3 1679.38  4948.6 1678.20  4987.8 1675.87
  4988.0 1675.37  4991.5 1675.37  4991.8 1675.87  5016.1 1676.48  5041.2 1676.59
  5051.5 1675.93  5058.0 1676.53  5092.7 1676.74  5123.5 1677.62  5133.8 1678.55
  5164.7 1682.74  5183.4 1686.06  5211.5 1689.86  5326.0 1692.60  5432.7 1693.51
#Mann=3,-1,0
  4754.8    0.05       0  4987.8    0.03       0  4991.8    0.05       0
Bank Sta=4987.8,4991.8
Exp/Cntr=0.3,0.1

Type RM Length L Ch R = 1,1480,179,179,179
BEGIN DESCRIPTION:
Elm 02 40 1480.47
END DESCRIPTION:
XS GIS Cut Line= 3
      1605683.31      6868882.98      1605540.09      6869142.08
      1605398.18      6869470.16
#Sta/Elev= 30
  4706.2 1694.92  4731.4 1694.78  4758.9 1692.61  4774.9 1692.34  4780.6 1691.49
  4791.0 1691.60  4796.7 1690.44  4812.7 1689.81  4818.4 1688.70  4834.5 1687.63
  4883.7 1682.10  4894.1 1681.97  4915.8 1680.28  4943.3 1676.48  4959.3 1675.49
  4974.7 1675.23  4984.8 1674.20  4985.1 1673.70  4988.6 1673.70  4988.8 1674.20
  5019.6 1674.86  5026.3 1674.39  5095.9 1677.01  5154.7 1680.94  5201.7 1685.64
  5215.7 1686.53  5277.6 1687.30  5283.0 1686.63  5353.5 1690.12  5359.7 1690.08
#Mann=3,-1,0
  4706.2    0.05       0  4984.8    0.03       0  4988.8    0.05       0
Bank Sta=4984.8,4988.8
Exp/Cntr=0.3,0.1

Type RM Length L Ch R = 1,1301,258,258,258
BEGIN DESCRIPTION:
Mapping XS d209adc3
END DESCRIPTION:
XS GIS Cut Line= 3
      1605669.71      6868852.44      1605461.38      6868977.43
      1605152.64      6869383.30
#Sta/Elev= 30
  4618.1 1694.90  4682.6 1693.52  4735.1 1690.35  4772.0 1688.94  4814.8 1685.35
  4830.3 1684.54  4836.2 1683.17  4856.7 1681.66  4880.2 1681.11  4894.8 1679.68
  4901.1 1679.70  4915.6 1678.44  4923.9 1676.71  4937.1 1675.26  4978.0 1673.62
  4978.3 1673.12  4981.8 1673.12  4982.0 1673.62  4994.6 1674.33  5115.2 1674.06
  5144.3 1674.96  5179.7 1677.47  5215.0 1679.36  5229.6 1679.61  5279.5 1682.41
  5323.1 1685.62  5343.9 1686.33  5358.5 1687.58  5364.7 1687.37  5371.0 1688.13
#Mann=3,-1,0
  4618.1    0.05       0  4978.0    0.03       0  4982.0    0.05       0
Bank Sta=4978,4982
Exp/Cntr=0.3,0.1

Type RM Length L Ch R = 1,1043,101,101,101
BEGIN DESCRIPTION:
Elm 02 40 1043.45
END DESCRIPTION:
XS GIS Cut Line= 3
      1605610.75      6868833.47      1605161.54      6868952.82
      1604935.81      6869132.98
#Sta/Elev= 30
  4541.6 1693.83  4576.1 1692.91  4581.2 1693.05  4588.9 1692.09  4599.3 1691.72
  4616.2 1690.58  4621.4 1690.53  4656.4 1688.66  4731.6 1685.35  4852.0 1682.97
  4868.3 1681.87  4887.0 1679.06  4892.2 1678.79  4909.7 1676.71  4927.2 1675.31
  4932.4 1675.19  4951.1 1672.97  5055.2 1672.89  5055.4 1672.39  5058.9 1672.39
  5059.2 1672.89  5086.0 1673.19  5106.8 1676.10  5114.8 1677.92  5121.2 1678.39
  5129.2 1680.36  5150.0 1681.50  5242.9 1683.08  5284.5 1683.52  5295.2 1683.33
#Mann=3,-1,0
  4541.6    0.05       0  5055.2    0.03       0  5059.2    0.05       0
Bank Sta=5055.2,5059.2
Exp/Cntr=0.3,0.1

Type RM Length L Ch R = 1,942,169,169,169
BEGIN DESCRIPTION:
Elm 02 40 941.84
END DESCRIPTION:
XS GIS Cut Line= 4
      1605385.04      6868540.53      1605105.12      6868874.70
      1605007.46      6868915.93      1604824.24      6869084.07
#Sta/Elev= 30
  4566.9 1687.87  4636.2 1684.18  4700.0 1683.50  4714.3 1680.94  4720.8 1681.65
  4728.6 1679.94  4749.4 1679.68  4757.2 1678.34  4798.8 1675.49  4941.9 1671.46
  4995.9 1671.39  4996.2 1670.89  4999.9 1671.39  5027.1 1672.17  5045.4 1671.52
  5057.2 1672.48  5074.5 1671.40  5098.2 1672.17  5107.4 1673.81  5119.1 1673.38
  5125.9 1676.03  5133.3 1674.95  5140.1 1676.56  5147.5 1675.48  5154.3 1676.83
  5161.7 1675.94  5182.6 1678.88  5211.0 1680.65  5302.9 1681.59  5357.5 1680.88
#Mann=3,-1,0
  4566.9    0.05       0  4995.9    0.05       0  4999.9    0.05       0
Bank Sta=4995.9,4999.9
Exp/Cntr=0.3,0.1

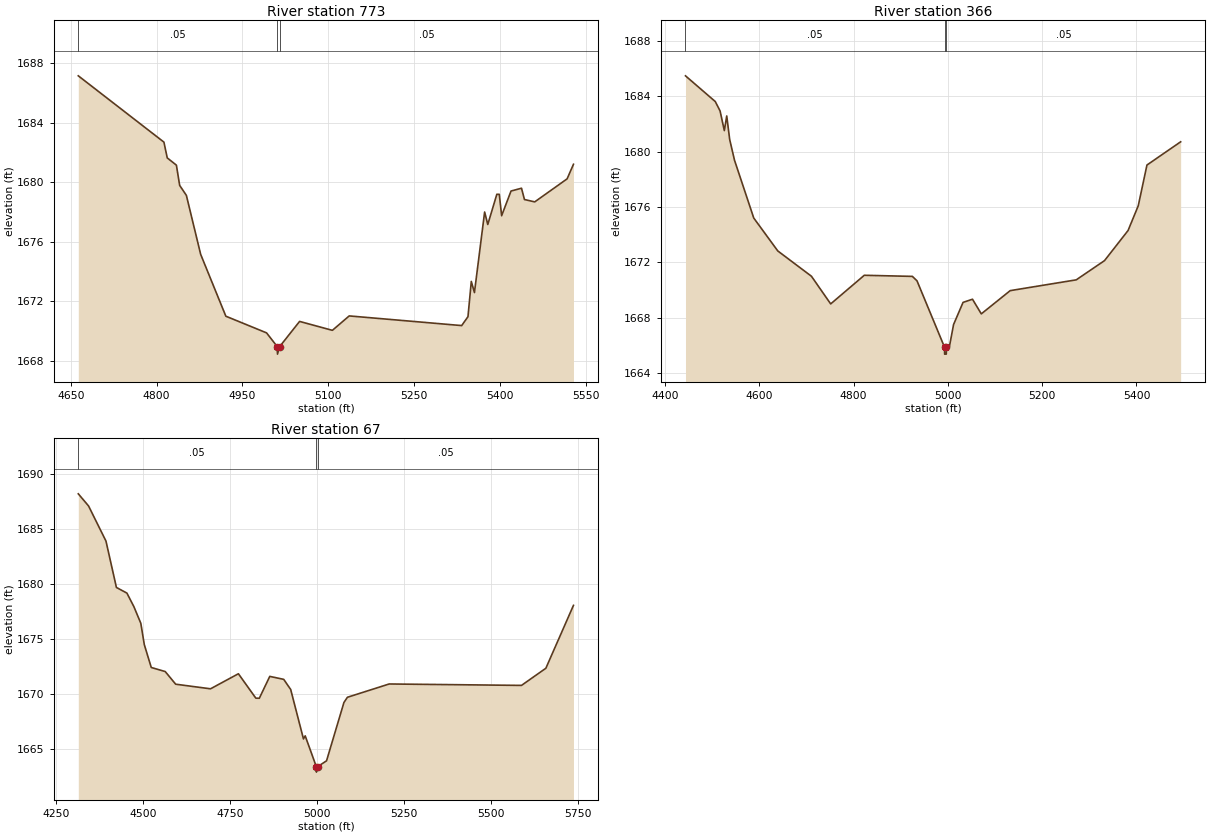
Type RM Length L Ch R = 1,773,407,407,407
BEGIN DESCRIPTION:
Mapping XS 2262fa07
END DESCRIPTION:
XS GIS Cut Line= 5
      1605339.82      6868539.95      1605176.66      6868630.21
      1604867.63      6868855.90      1604801.66      6869005.21
      1604767.03      6869133.35
#Sta/Elev= 30
  4663.2 1687.16  4812.8 1682.70  4818.6 1681.64  4834.6 1681.15  4840.3 1679.79
  4852.0 1679.12  4877.0 1675.15  4921.0 1670.99  4992.1 1669.87  5010.9 1668.94
  5011.2 1668.44  5014.9 1668.94  5049.8 1670.64  5107.1 1670.04  5136.5 1671.01
  5333.0 1670.36  5344.0 1670.96  5349.8 1673.33  5355.3 1672.58  5373.1 1678.00
  5378.6 1677.16  5394.4 1679.19  5398.7 1679.19  5402.8 1677.75  5419.2 1679.41
  5437.5 1679.60  5442.7 1678.84  5460.6 1678.68  5517.2 1680.23  5528.3 1681.21
#Mann=3,-1,0
  4663.2    0.05       0  5010.9    0.05       0  5014.9    0.05       0
Bank Sta=5010.9,5014.9
Exp/Cntr=0.3,0.1

Type RM Length L Ch R = 1,366,299,299,299
BEGIN DESCRIPTION:
Elm 02 40 366.44
END DESCRIPTION:
XS GIS Cut Line= 3
      1605257.03      6868536.16      1604712.32      6868644.67
      1604697.13      6869139.42
#Sta/Elev= 30
  4443.4 1685.48  4506.6 1683.62  4516.8 1682.94  4525.8 1681.52  4530.9 1682.58
  4537.2 1680.87  4547.4 1679.38  4588.2 1675.20  4639.2 1672.82  4710.6 1670.99
  4751.4 1668.99  4822.7 1671.06  4924.7 1670.98  4934.5 1670.66  4992.9 1665.86
  4993.1 1665.36  4996.6 1665.36  4996.9 1665.86  5003.0 1665.86  5012.1 1667.50
  5032.2 1669.10  5052.2 1669.33  5070.9 1668.27  5132.2 1669.95  5272.3 1670.73
  5332.3 1672.12  5382.3 1674.30  5403.9 1676.09  5422.3 1679.03  5493.8 1680.71
#Mann=3,-1,0
  4443.4    0.05       0  4992.9    0.05       0  4996.9    0.05       0
Bank Sta=4992.9,4996.9
Exp/Cntr=0.3,0.1

Type RM Length L Ch R = 1,67,0,0,0
BEGIN DESCRIPTION:
Elm 02 40 1486.064
END DESCRIPTION:
XS GIS Cut Line= 3
      1605254.42      6868433.29      1604568.87      6868401.23
      1604573.44      6869137.32
#Sta/Elev= 30
  4313.7 1688.24  4343.1 1687.14  4393.2 1683.94  4423.2 1679.72  4453.3 1679.21
  4473.3 1677.98  4493.3 1676.46  4503.3 1674.52  4523.3 1672.44  4563.4 1672.07
  4593.4 1670.92  4693.5 1670.50  4773.6 1671.87  4823.7 1669.65  4833.7 1669.64
  4863.7 1671.63  4903.8 1671.36  4923.8 1670.44  4960.5 1665.94  4965.5 1666.22
  4997.4 1663.42  4997.7 1662.92  5001.4 1663.42  5026.8 1663.95  5076.8 1669.26
  5086.8 1669.73  5206.8 1670.94  5586.8 1670.81  5656.8 1672.37  5736.1 1678.09
#Mann=3,-1,0
  4313.7    0.05       0  4997.4    0.05       0  5001.4    0.05       0
Bank Sta=4997.4,5001.4
Exp/Cntr=0.3,0.1

Chan Stop Cuts=-1