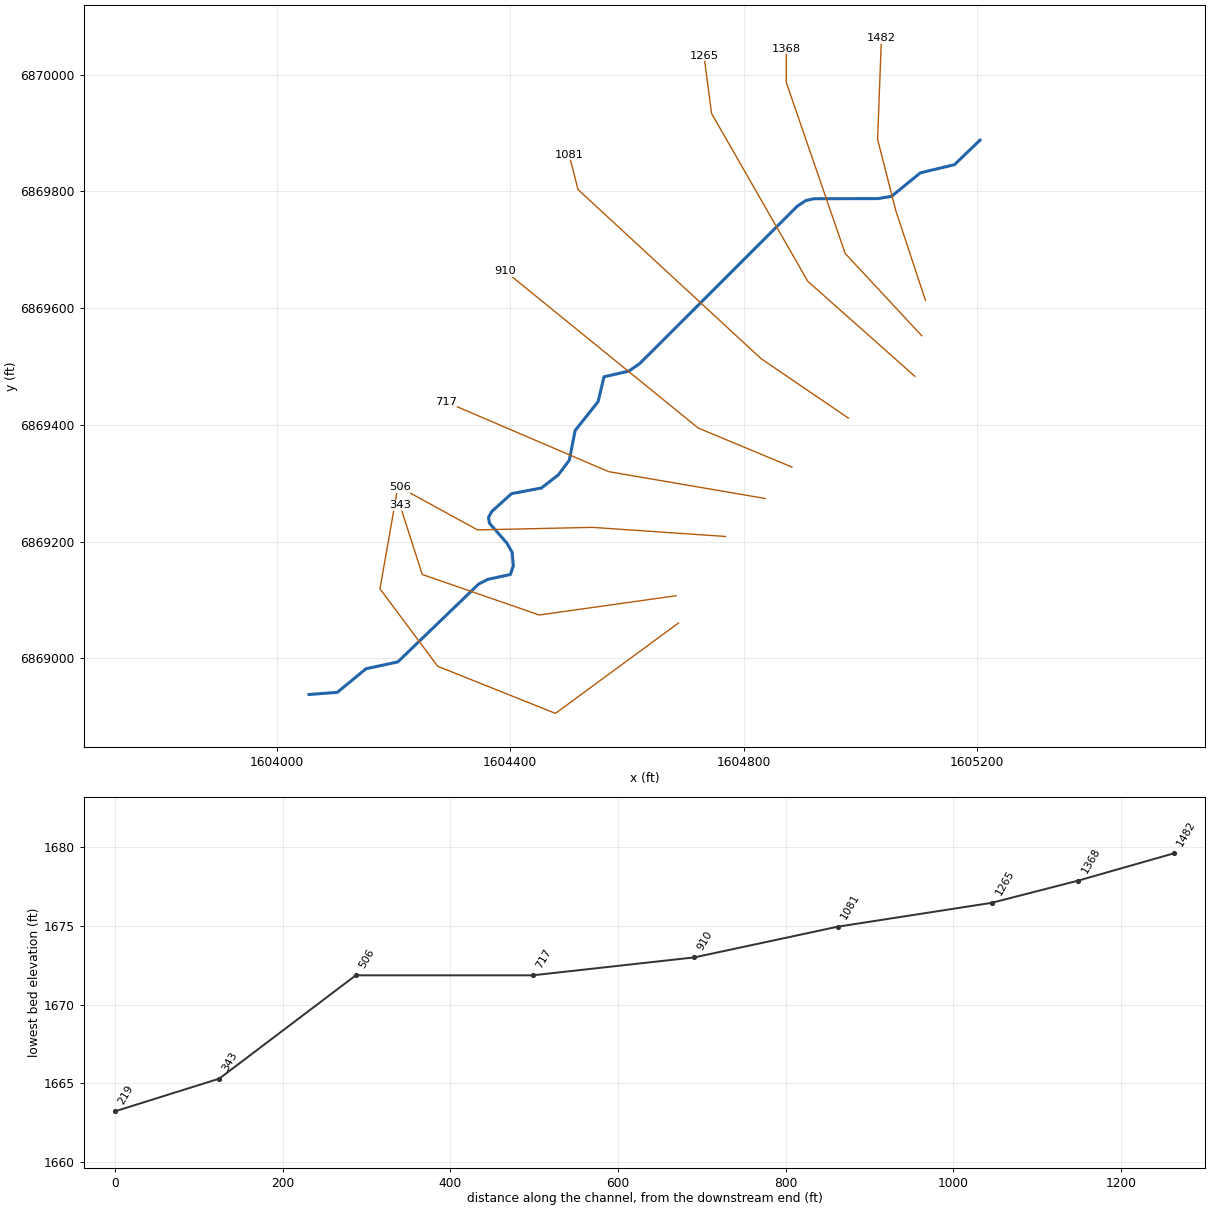
--- Elm 02 41.prj (project) ---

Proj Title=Elm 02 41 Base Level Engineering
Current Plan=p01
Default Exp/Contr=0.3,0.1
English Units
Geom File=g01
Flow File=f01
Plan File=p01
BEGIN DESCRIPTION:
Elm 02 41
END DESCRIPTION:

--- Elm 02 41.p01 (plan) ---

Plan Title=Multiple Run
Short Identifier=Multiple
Geom File=g01
Flow File=f01
Subcritical Flow
K Sum by GR= 0
Std Step Tol= 0.01
Critical Tol= 0.01
Num of Std Step Trials= 20
Max Error Tol= 0.3
Flow Tol Ratio= 0.001
Split Flow NTrial= 30
Split Flow Tol= 0.02
Split Flow Ratio= 0.02
Log Output Level= 0
Friction Slope Method= 1
Unsteady Friction Slope Method= 2
Unsteady Bridges Friction Slope Method= 1
Parabolic Critical Depth
Global Vel Dist=  1 , 1 , 1
Global Log Level= 0
CheckData=True
Encroach Param= -1, 0, 0, 0
BEGIN DESCRIPTION:
Multiple Run
END DESCRIPTION:

--- Elm 02 41.f01 (steady flow) ---

Flow Title=Multiple
Number of Profiles=7
Profile Names=10-year,25-year,50-year,1pct_min,100-year,1pct_plu,500-year
River Rch & RM= Elm 02 41,Reach-1,1482
      56      71      82      59      94     130     127
Boundary for River Rch & Prof#=Elm 02 41,Reach-1,1
Up Type=0
Dn Type=3
Dn Slope=0.001
Boundary for River Rch & Prof#=Elm 02 41,Reach-1,2
Up Type=0
Dn Type=3
Dn Slope=0.001
Boundary for River Rch & Prof#=Elm 02 41,Reach-1,3
Up Type=0
Dn Type=3
Dn Slope=0.001
Boundary for River Rch & Prof#=Elm 02 41,Reach-1,4
Up Type=0
Dn Type=3
Dn Slope=0.001
Boundary for River Rch & Prof#=Elm 02 41,Reach-1,5
Up Type=0
Dn Type=3
Dn Slope=0.001
Boundary for River Rch & Prof#=Elm 02 41,Reach-1,6
Up Type=0
Dn Type=3
Dn Slope=0.001
Boundary for River Rch & Prof#=Elm 02 41,Reach-1,7
Up Type=0
Dn Type=3
Dn Slope=0.001

--- Elm 02 41.g01 (geometry) ---

Geom Title=Existing Conditions

River Reach=Elm 02 41,Reach-1
Reach XY= 30
      1605205.00      6869888.00      1605161.15      6869845.91
      1605102.78      6869831.97      1605053.45      6869791.75
      1605030.08      6869787.81      1604920.16      6869787.60
      1604906.47      6869784.46      1604891.68      6869774.63
      1604621.48      6869504.73      1604602.99      6869492.13
      1604560.59      6869482.39      1604550.66      6869440.10
      1604511.10      6869390.20      1604501.14      6869339.42
      1604482.13      6869314.16      1604453.51      6869291.89
      1604402.18      6869282.14      1604368.40      6869251.72
      1604362.73      6869241.63      1604364.29      6869231.56
      1604394.17      6869197.44      1604403.17      6869181.58
      1604405.23      6869158.37      1604400.19      6869143.62
      1604361.62      6869135.31      1604345.67      6869127.11
      1604207.31      6868993.82      1604152.76      6868982.03
      1604103.51      6868941.60      1604055.00      6868938.00

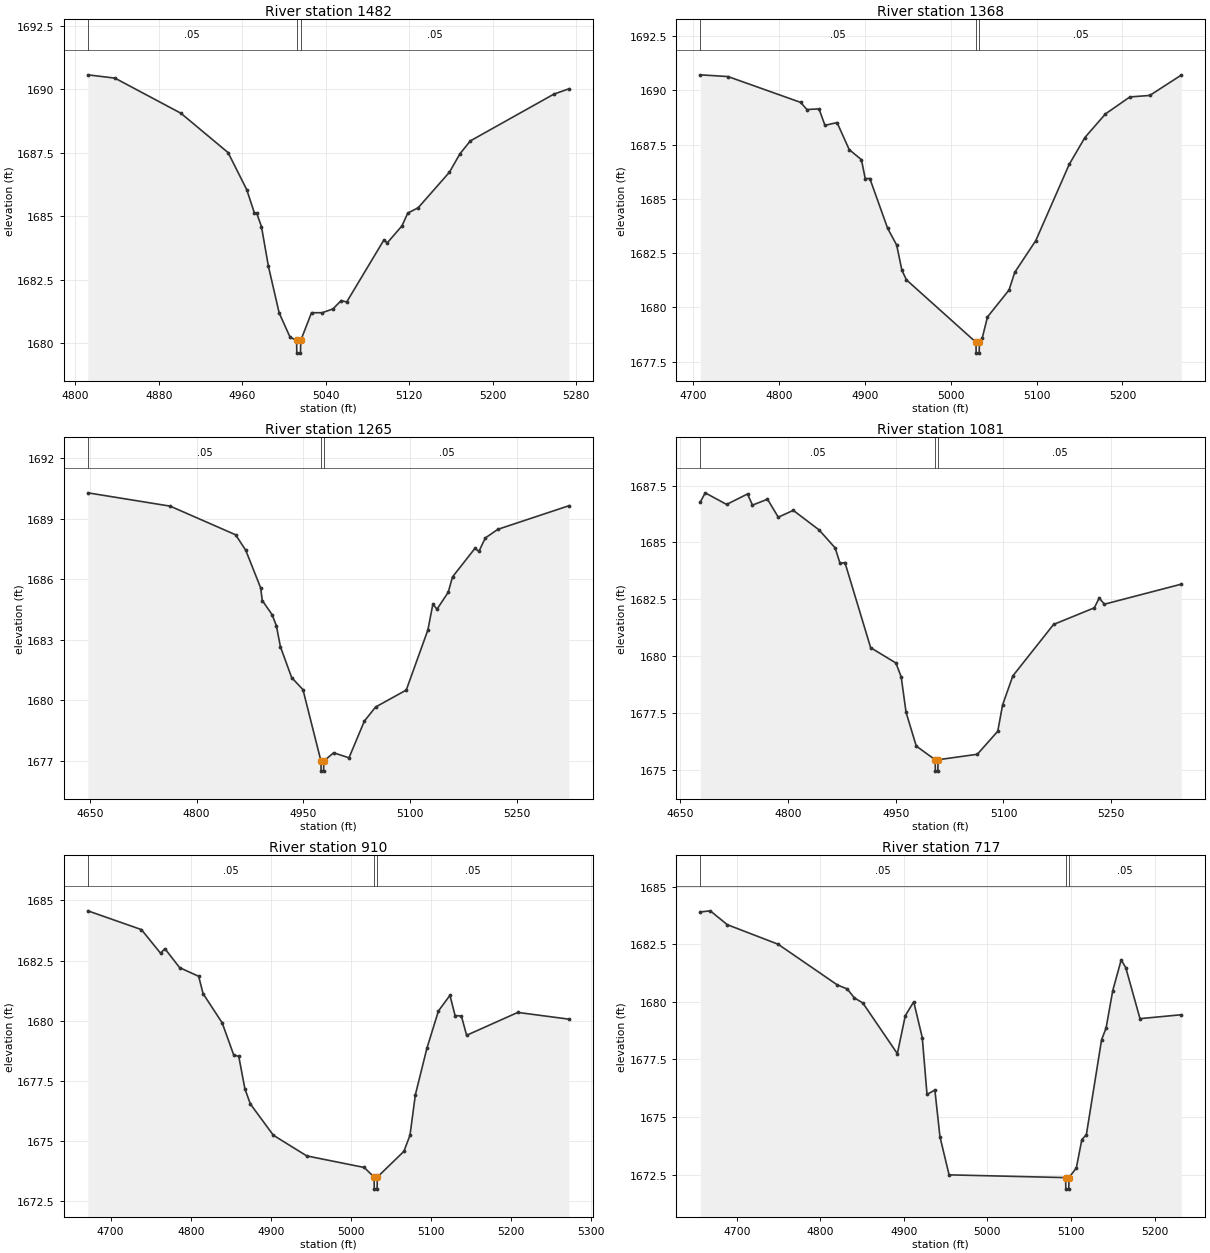
Type RM Length L Ch R = 1,1482,114,114,114
BEGIN DESCRIPTION:
Elm 02 41 2.0
END DESCRIPTION:
XS GIS Cut Line= 4
      1605111.55      6869613.31      1605060.78      6869766.93
      1605029.53      6869889.32      1605036.04      6870062.49
#Sta/Elev= 30
  4811.9 1690.57  4837.9 1690.44  4901.1 1689.06  4946.4 1687.51  4964.3 1686.05
  4971.6 1685.14  4973.7 1685.14  4978.4 1684.60  4985.1 1683.03  4995.4 1681.20
  5005.8 1680.25  5012.1 1680.12  5012.3 1679.62  5015.8 1679.62  5016.1 1680.12
  5026.4 1681.21  5036.7 1681.21  5047.0 1681.36  5054.9 1681.69  5060.1 1681.63
  5095.8 1684.07  5099.1 1683.96  5113.2 1684.63  5118.7 1685.13  5128.7 1685.34
  5158.7 1686.74  5168.7 1687.46  5178.7 1687.97  5258.8 1689.81  5273.3 1690.02
#Mann=3,-1,0
  4811.9    0.05       0  5012.1    0.05       0  5016.1    0.05       0
Bank Sta=5012.1,5016.1
Exp/Cntr=0.3,0.1

Type RM Length L Ch R = 1,1368,103,103,103
BEGIN DESCRIPTION:
Mapping XS 42c96b93
END DESCRIPTION:
XS GIS Cut Line= 4
      1605105.29      6869552.71      1604973.97      6869693.79
      1604873.06      6869986.76      1604873.06      6870044.76
#Sta/Elev= 30
  4708.0 1690.72  4740.4 1690.64  4824.9 1689.45  4832.3 1689.12  4846.4 1689.15
  4853.3 1688.39  4867.4 1688.52  4881.6 1687.27  4895.8 1686.81  4900.2 1685.94
  4905.6 1685.94  4926.3 1683.65  4936.9 1682.87  4942.9 1681.72  4948.2 1681.27
  5029.3 1678.39  5029.5 1677.89  5033.0 1677.89  5033.3 1678.39  5036.6 1678.59
  5042.7 1679.56  5067.8 1680.80  5074.4 1681.61  5099.0 1683.08  5137.9 1686.59
  5156.2 1687.83  5180.2 1688.92  5208.6 1689.70  5231.8 1689.77  5268.6 1690.71
#Mann=3,-1,0
  4708.0    0.05       0  5029.3    0.05       0  5033.3    0.05       0
Bank Sta=5029.3,5033.3
Exp/Cntr=0.3,0.1

Type RM Length L Ch R = 1,1265,184,184,184
BEGIN DESCRIPTION:
Mapping XS e31e54f2
END DESCRIPTION:
XS GIS Cut Line= 4
      1605093.33      6869483.29      1604909.95      6869646.05
      1604745.02      6869933.59      1604732.00      6870032.36
#Sta/Elev= 30
  4647.2 1690.28  4762.9 1689.62  4854.9 1688.20  4869.2 1687.43  4890.1 1685.57
  4892.4 1684.94  4906.2 1684.24  4912.2 1683.69  4917.9 1682.65  4933.7 1681.12
  4949.6 1680.52  4974.9 1676.98  4975.1 1676.48  4978.6 1676.48  4978.9 1676.98
  4992.7 1677.39  5014.3 1677.14  5035.9 1678.96  5051.7 1679.66  5094.8 1680.50
  5125.2 1683.48  5132.2 1684.76  5138.0 1684.51  5153.8 1685.35  5159.8 1686.11
  5191.2 1687.52  5197.0 1687.38  5205.9 1688.04  5223.5 1688.47  5323.5 1689.64
#Mann=3,-1,0
  4647.2    0.05       0  4974.9    0.05       0  4978.9    0.05       0
Bank Sta=4974.9,4978.9
Exp/Cntr=0.3,0.1

Type RM Length L Ch R = 1,1081,171,171,171
BEGIN DESCRIPTION:
Mapping XS 9b3c9355
END DESCRIPTION:
XS GIS Cut Line= 4
      1604979.41      6869411.67      1604829.66      6869513.67
      1604516.07      6869803.39      1604500.88      6869863.06
#Sta/Elev= 30
  4677.9 1686.77  4684.8 1687.18  4714.6 1686.67  4743.7 1687.13  4750.6 1686.64
  4771.5 1686.90  4786.5 1686.11  4807.4 1686.41  4843.4 1685.55  4865.7 1684.76
  4872.5 1684.08  4879.3 1684.12  4915.1 1680.38  4950.2 1679.71  4957.6 1679.10
  4964.4 1677.54  4978.6 1676.06  5004.9 1675.46  5005.2 1674.96  5008.7 1674.96
  5008.9 1675.46  5063.6 1675.70  5092.0 1676.71  5098.8 1677.87  5113.0 1679.14
  5169.7 1681.40  5226.4 1682.13  5233.2 1682.56  5240.5 1682.29  5347.6 1683.17
#Mann=3,-1,0
  4677.9    0.05       0  5004.9    0.05       0  5008.9    0.05       0
Bank Sta=5004.9,5008.9
Exp/Cntr=0.3,0.1

Type RM Length L Ch R = 1,910,193,193,193
BEGIN DESCRIPTION:
Mapping XS 20ef143c
END DESCRIPTION:
XS GIS Cut Line= 3
      1604882.80      6869327.70      1604722.23      6869394.53
      1604390.93      6869663.72
#Sta/Elev= 30
  4671.5 1684.57  4738.4 1683.79  4762.3 1682.81  4767.7 1683.00  4786.1 1682.21
  4809.9 1681.85  4815.4 1681.13  4839.2 1679.92  4853.6 1678.59  4860.0 1678.52
  4867.6 1677.18  4874.4 1676.55  4903.1 1675.25  4944.9 1674.39  5016.6 1673.91
  5029.0 1673.51  5029.2 1673.01  5032.7 1673.01  5033.0 1673.51  5066.2 1674.58
  5073.8 1675.25  5080.5 1676.93  5094.9 1678.86  5109.3 1680.41  5123.7 1681.06
  5130.1 1680.22  5138.0 1680.20  5144.5 1679.40  5208.4 1680.35  5272.3 1680.07
#Mann=3,-1,0
  4671.5    0.05       0  5029.0    0.03       0  5033.0    0.05       0
Bank Sta=5029,5033
Exp/Cntr=0.3,0.1

Type RM Length L Ch R = 1,717,211,211,211
BEGIN DESCRIPTION:
Mapping XS 5199204a
END DESCRIPTION:
XS GIS Cut Line= 3
      1604836.83      6869273.87      1604568.59      6869319.88
      1604289.50      6869439.49
#Sta/Elev= 30
  4656.3 1683.90  4668.3 1683.95  4688.6 1683.35  4749.5 1682.50  4820.5 1680.73
  4832.2 1680.56  4840.8 1680.17  4850.9 1679.95  4892.2 1677.75  4901.7 1679.40
  4911.8 1680.00  4922.0 1678.45  4927.7 1675.98  4937.1 1676.17  4943.2 1674.14
  4954.1 1672.49  5093.6 1672.37  5093.8 1671.87  5097.3 1671.87  5097.6 1672.37
  5106.4 1672.79  5113.0 1674.02  5118.4 1674.23  5136.6 1678.35  5142.0 1678.86
  5150.0 1680.49  5160.1 1681.82  5165.6 1681.48  5182.6 1679.27  5232.1 1679.44
#Mann=3,-1,0
  4656.3    0.05       0  5093.6    0.03       0  5097.6    0.05       0
Bank Sta=5093.6,5097.6
Exp/Cntr=0.3,0.1

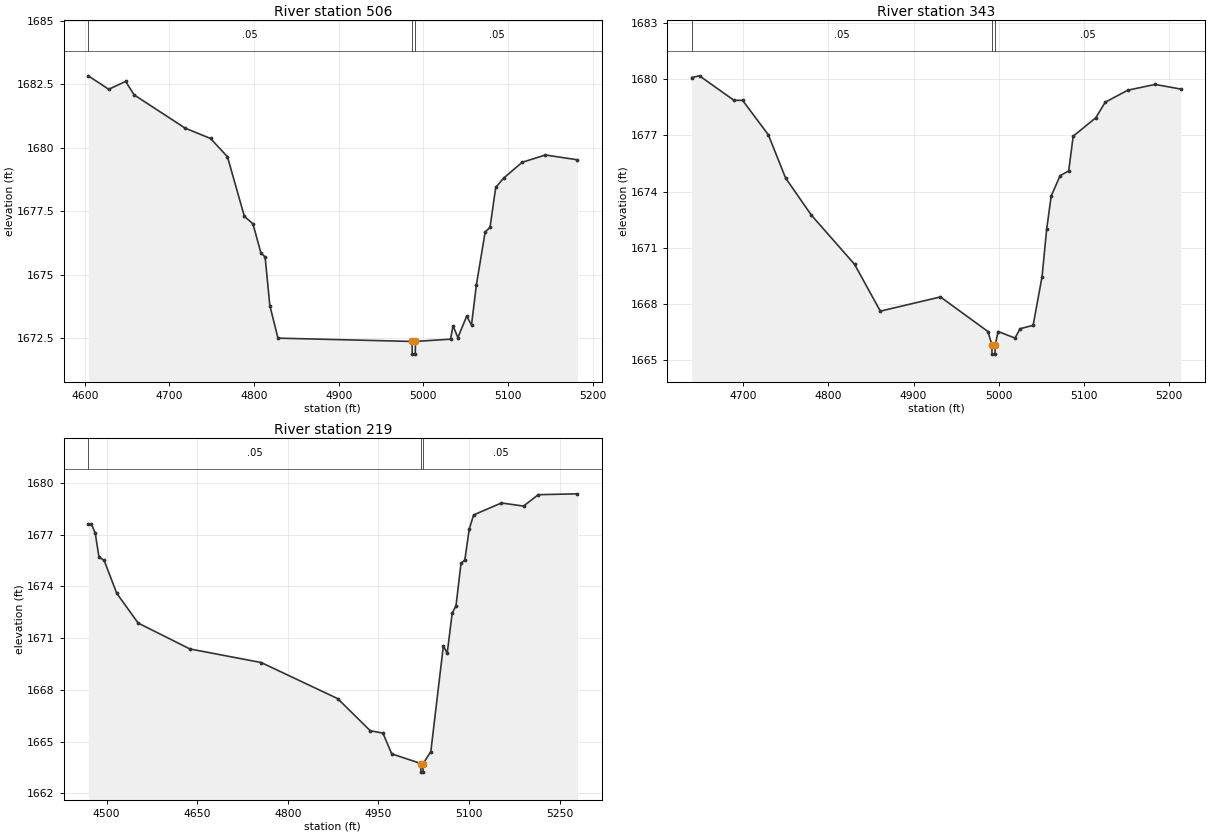
Type RM Length L Ch R = 1,506,163,163,163
BEGIN DESCRIPTION:
Mapping XS d4c2d207
END DESCRIPTION:
XS GIS Cut Line= 4
      1604769.11      6869208.77      1604540.81      6869224.39
      1604343.76      6869220.05      1604210.34      6869293.22
#Sta/Elev= 30
  4604.1 1682.84  4628.3 1682.31  4648.3 1682.62  4658.3 1682.09  4718.5 1680.78
  4748.6 1680.37  4768.6 1679.65  4788.6 1677.30  4798.7 1677.01  4808.1 1675.86
  4813.1 1675.70  4818.7 1673.78  4828.3 1672.50  4986.8 1672.37  4987.0 1671.87
  4990.5 1671.87  4990.8 1672.37  5032.2 1672.46  5035.2 1672.99  5040.9 1672.52
  5051.3 1673.37  5057.0 1673.02  5062.8 1674.61  5073.1 1676.68  5078.9 1676.87
  5085.6 1678.44  5095.0 1678.81  5116.8 1679.43  5144.3 1679.72  5182.2 1679.53
#Mann=3,-1,0
  4604.1    0.05       0  4986.8    0.05       0  4990.8    0.05       0
Bank Sta=4986.8,4990.8
Exp/Cntr=0.3,0.1

Type RM Length L Ch R = 1,343,124,124,124
BEGIN DESCRIPTION:
Mapping XS 5617a89a
END DESCRIPTION:
XS GIS Cut Line= 4
      1604684.04      6869107.21      1604449.66      6869074.22
      1604249.14      6869143.66      1604210.95      6869262.59
#Sta/Elev= 30
  4639.9 1680.10  4649.0 1680.19  4689.4 1678.88  4699.5 1678.88  4729.8 1677.03
  4750.0 1674.72  4780.3 1672.73  4830.8 1670.11  4861.1 1667.60  4931.6 1668.36
  4987.3 1666.51  4991.9 1665.80  4992.1 1665.30  4995.6 1665.30  4995.9 1665.80
  4999.2 1666.51  5019.1 1666.16  5025.0 1666.66  5040.3 1666.84  5050.8 1669.45
  5056.2 1671.99  5061.5 1673.76  5072.0 1674.85  5082.0 1675.10  5087.3 1676.96
  5113.9 1677.95  5124.9 1678.78  5151.3 1679.42  5183.4 1679.73  5213.7 1679.48
#Mann=3,-1,0
  4639.9    0.05       0  4991.9    0.05       0  4995.9    0.05       0
Bank Sta=4991.9,4995.9
Exp/Cntr=0.3,0.1

Type RM Length L Ch R = 1,219,0,0,0
BEGIN DESCRIPTION:
Elm 02 41 1.0
END DESCRIPTION:
XS GIS Cut Line= 5
      1604688.36      6869060.53      1604477.44      6868905.60
      1604275.62      6868986.33      1604176.66      6869119.14
      1604205.31      6869281.93
#Sta/Elev= 30
  4469.7 1677.62  4474.9 1677.62  4481.3 1677.07  4487.5 1675.69  4495.9 1675.51
  4516.8 1673.60  4552.3 1671.87  4637.9 1670.37  4756.2 1669.58  4882.7 1667.49
  4936.6 1665.63  4957.6 1665.49  4972.2 1664.29  5020.3 1663.73  5020.5 1663.23
  5024.0 1663.23  5024.3 1663.73  5036.9 1664.42  5057.7 1670.56  5064.0 1670.11
  5072.3 1672.45  5078.6 1672.87  5086.9 1675.33  5093.2 1675.53  5100.5 1677.31
  5107.8 1678.14  5153.9 1678.83  5190.4 1678.65  5214.8 1679.31  5279.7 1679.36
#Mann=3,-1,0
  4469.7    0.05       0  5020.3    0.05       0  5024.3    0.05       0
Bank Sta=5020.3,5024.3
Exp/Cntr=0.3,0.1

Chan Stop Cuts=-1