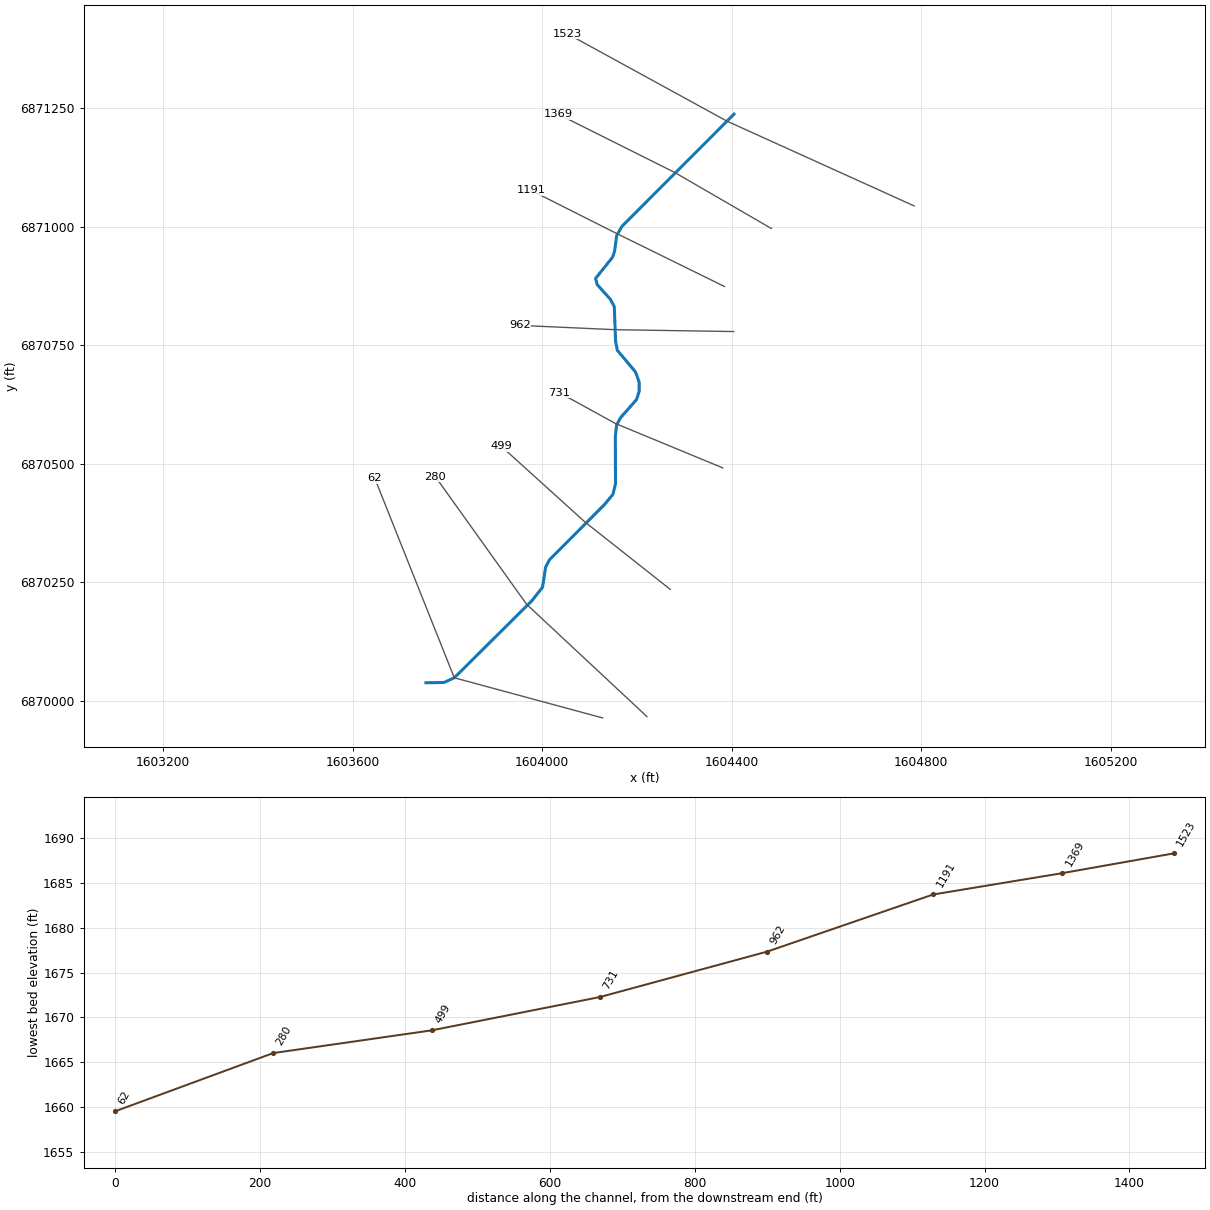
--- Elm 02 42.prj (project) ---

Proj Title=Elm 02 42 Base Level Engineering
Current Plan=p01
Default Exp/Contr=0.3,0.1
English Units
Geom File=g01
Flow File=f01
Plan File=p01
BEGIN DESCRIPTION:
Elm 02 42
END DESCRIPTION:

--- Elm 02 42.p01 (plan) ---

Plan Title=Multiple Run
Short Identifier=Multiple
Geom File=g01
Flow File=f01
Subcritical Flow
K Sum by GR= 0
Std Step Tol= 0.01
Critical Tol= 0.01
Num of Std Step Trials= 20
Max Error Tol= 0.3
Flow Tol Ratio= 0.001
Split Flow NTrial= 30
Split Flow Tol= 0.02
Split Flow Ratio= 0.02
Log Output Level= 0
Friction Slope Method= 1
Unsteady Friction Slope Method= 2
Unsteady Bridges Friction Slope Method= 1
Parabolic Critical Depth
Global Vel Dist=  1 , 1 , 1
Global Log Level= 0
CheckData=True
Encroach Param= -1, 0, 0, 0
BEGIN DESCRIPTION:
Multiple Run
END DESCRIPTION:

--- Elm 02 42.f01 (steady flow) ---

Flow Title=Multiple
Number of Profiles=7
Profile Names=10-year,25-year,50-year,1pct_min,100-year,1pct_plu,500-year
River Rch & RM= Elm 02 42,Reach-1,1523
      57      72      83      60      96     132     130
Boundary for River Rch & Prof#=Elm 02 42,Reach-1,1
Up Type=0
Dn Type=3
Dn Slope=0.001
Boundary for River Rch & Prof#=Elm 02 42,Reach-1,2
Up Type=0
Dn Type=3
Dn Slope=0.001
Boundary for River Rch & Prof#=Elm 02 42,Reach-1,3
Up Type=0
Dn Type=3
Dn Slope=0.001
Boundary for River Rch & Prof#=Elm 02 42,Reach-1,4
Up Type=0
Dn Type=3
Dn Slope=0.001
Boundary for River Rch & Prof#=Elm 02 42,Reach-1,5
Up Type=0
Dn Type=3
Dn Slope=0.001
Boundary for River Rch & Prof#=Elm 02 42,Reach-1,6
Up Type=0
Dn Type=3
Dn Slope=0.001
Boundary for River Rch & Prof#=Elm 02 42,Reach-1,7
Up Type=0
Dn Type=3
Dn Slope=0.001

--- Elm 02 42.g01 (geometry) ---

Geom Title=Existing Conditions

River Reach=Elm 02 42,Reach-1
Reach XY= 30
      1604405.00      6871238.00      1604227.70      6871060.41
      1604168.61      6871001.21      1604157.46      6870981.95
      1604153.12      6870948.64      1604148.59      6870935.72
      1604113.04      6870891.32      1604116.45      6870878.10
      1604143.75      6870847.78      1604152.45      6870832.11
      1604155.25      6870758.10      1604158.88      6870739.59
      1604197.19      6870693.92      1604204.91      6870672.61
      1604204.91      6870653.39      1604199.62      6870635.82
      1604165.91      6870597.67      1604157.30      6870582.07
      1604154.68      6870558.14      1604155.02      6870457.99
      1604149.53      6870435.55      1604132.14      6870414.47
      1604015.78      6870297.68      1604007.54      6870281.95
      1604001.02      6870239.65      1603978.70      6870211.18
      1603924.06      6870156.96      1603814.79      6870048.51
      1603793.16      6870038.59      1603755.00      6870038.00

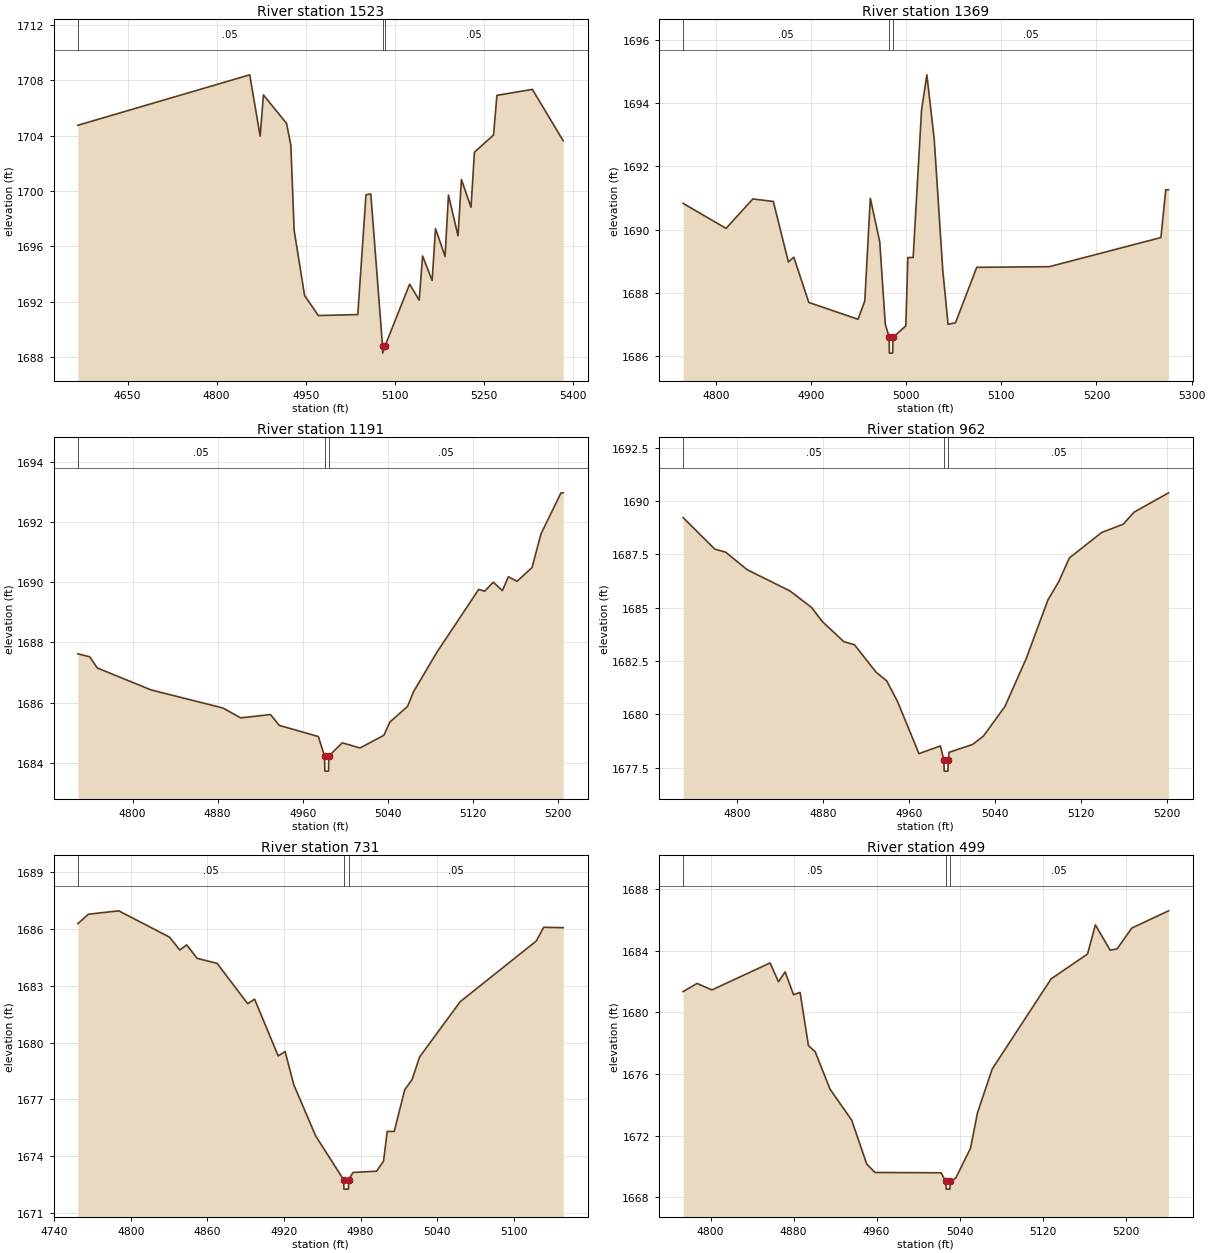
Type RM Length L Ch R = 1,1523,154,154,154
BEGIN DESCRIPTION:
Elm 02 42 1376.72
END DESCRIPTION:
XS GIS Cut Line= 3
      1604785.29      6871044.27      1604390.23      6871223.20
      1604053.58      6871407.52
#Sta/Elev= 30
  4566.3 1704.74  4855.8 1708.38  4873.4 1703.96  4878.9 1706.93  4917.9 1704.87
  4925.1 1703.30  4930.6 1697.17  4948.2 1692.47  4971.3 1691.02  5037.8 1691.09
  5051.6 1699.73  5059.7 1699.79  5079.5 1688.81  5079.7 1688.31  5083.5 1688.81
  5125.1 1693.28  5141.2 1692.13  5146.9 1695.32  5163.0 1693.55  5168.7 1697.29
  5184.8 1695.28  5190.5 1699.71  5206.6 1696.77  5212.3 1700.83  5228.5 1698.83
  5234.2 1702.80  5266.4 1704.04  5272.1 1706.90  5331.8 1707.33  5383.8 1703.62
#Mann=3,-1,0
  4566.3    0.05       0  5079.5    0.03       0  5083.5    0.05       0
Bank Sta=5079.5,5083.5
Exp/Cntr=0.3,0.1

Type RM Length L Ch R = 1,1369,178,178,178
BEGIN DESCRIPTION:
Elm 02 42 1368.96
END DESCRIPTION:
XS GIS Cut Line= 3
      1604484.03      6870996.62      1604279.61      6871115.11
      1604034.79      6871237.52
#Sta/Elev= 30
  4765.7 1690.83  4810.8 1690.04  4839.0 1690.97  4860.5 1690.89  4876.3 1688.98
  4882.0 1689.13  4897.8 1687.70  4949.5 1687.17  4956.6 1687.75  4962.4 1690.99
  4972.3 1689.62  4978.1 1687.02  4982.2 1686.60  4982.4 1686.10  4985.9 1686.10
  4986.2 1686.60  4999.7 1686.96  5001.8 1689.12  5007.4 1689.12  5016.2 1693.77
  5021.8 1694.89  5029.5 1692.87  5038.5 1688.72  5044.1 1687.01  5051.9 1687.06
  5074.2 1688.81  5150.3 1688.83  5267.7 1689.75  5272.8 1691.26  5275.7 1691.26
#Mann=3,-1,0
  4765.7    0.05       0  4982.2    0.03       0  4986.2    0.05       0
Bank Sta=4982.2,4986.2
Exp/Cntr=0.3,0.1

Type RM Length L Ch R = 1,1191,229,229,229
BEGIN DESCRIPTION:
Elm 02 42 1190.89
END DESCRIPTION:
XS GIS Cut Line= 3
      1604385.03      6870874.24      1604157.21      6870986.20
      1603976.21      6871077.35
#Sta/Elev= 30
  4748.5 1687.62  4759.7 1687.52  4766.8 1687.15  4817.3 1686.42  4884.8 1685.82
  4901.7 1685.49  4929.7 1685.60  4938.0 1685.24  4974.7 1684.87  4980.5 1684.22
  4980.8 1683.72  4984.3 1683.72  4984.5 1684.22  4997.2 1684.66  5013.9 1684.49
  5036.3 1684.91  5041.9 1685.35  5058.6 1685.87  5064.2 1686.36  5086.5 1687.69
  5125.5 1689.76  5131.1 1689.70  5139.2 1690.00  5147.8 1689.72  5153.4 1690.18
  5161.6 1690.03  5175.7 1690.49  5184.0 1691.60  5202.9 1692.97  5205.0 1692.97
#Mann=3,-1,0
  4748.5    0.05       0  4980.5    0.05       0  4984.5    0.05       0
Bank Sta=4980.5,4984.5
Exp/Cntr=0.3,0.1

Type RM Length L Ch R = 1,962,231,231,231
BEGIN DESCRIPTION:
Elm 02 42 961.59
END DESCRIPTION:
XS GIS Cut Line= 3
      1604404.57      6870779.17      1604154.61      6870783.08
      1603952.81      6870792.19
#Sta/Elev= 30
  4749.7 1689.22  4779.3 1687.74  4789.3 1687.60  4809.3 1686.78  4849.3 1685.78
  4869.3 1685.01  4879.3 1684.35  4899.3 1683.41  4909.3 1683.26  4929.3 1681.98
  4939.3 1681.57  4949.3 1680.61  4969.3 1678.16  4989.3 1678.52  4992.6 1677.84
  4992.8 1677.34  4996.3 1677.34  4996.6 1677.84  4997.3 1678.22  5019.3 1678.59
  5029.3 1678.98  5049.4 1680.37  5069.4 1682.64  5089.4 1685.36  5099.4 1686.21
  5109.4 1687.33  5139.4 1688.52  5159.5 1688.91  5169.5 1689.47  5201.7 1690.38
#Mann=3,-1,0
  4749.7    0.05       0  4992.6    0.03       0  4996.6    0.05       0
Bank Sta=4992.6,4996.6
Exp/Cntr=0.3,0.1

Type RM Length L Ch R = 1,731,232,232,232
BEGIN DESCRIPTION:
Elm 02 42 731.08
END DESCRIPTION:
XS GIS Cut Line= 3
      1604381.38      6870491.43      1604154.87      6870585.16
      1604036.41      6870650.24
#Sta/Elev= 30
  4758.5 1686.29  4766.7 1686.79  4790.6 1686.97  4830.3 1685.58  4838.4 1684.90
  4843.8 1685.17  4852.0 1684.46  4867.7 1684.19  4891.6 1682.06  4897.0 1682.30
  4915.5 1679.30  4920.9 1679.53  4927.7 1677.78  4944.8 1675.08  4966.7 1672.76
  4967.0 1672.26  4970.5 1672.26  4970.7 1672.76  4974.1 1673.14  4992.6 1673.21
  4998.0 1673.74  5000.9 1675.31  5006.4 1675.31  5014.6 1677.51  5020.3 1678.04
  5026.3 1679.25  5058.1 1682.17  5117.6 1685.37  5123.5 1686.10  5138.8 1686.08
#Mann=3,-1,0
  4758.5    0.05       0  4966.7    0.03       0  4970.7    0.05       0
Bank Sta=4966.7,4970.7
Exp/Cntr=0.3,0.1

Type RM Length L Ch R = 1,499,219,219,219
BEGIN DESCRIPTION:
Elm 02 42 499.12
END DESCRIPTION:
XS GIS Cut Line= 3
      1604270.73      6870234.92      1604091.06      6870376.83
      1603913.99      6870536.98
#Sta/Elev= 30
  4773.6 1681.35  4787.0 1681.88  4801.4 1681.46  4857.4 1683.21  4865.5 1681.99
  4871.9 1682.63  4880.0 1681.15  4886.3 1681.30  4894.4 1677.84  4900.8 1677.46
  4915.2 1675.02  4936.0 1673.02  4950.5 1670.17  4958.5 1669.62  5022.1 1669.60
  5026.8 1669.04  5027.1 1668.54  5030.6 1668.54  5030.8 1669.04  5036.3 1669.26
  5050.5 1671.19  5057.2 1673.48  5071.4 1676.33  5128.2 1682.18  5163.3 1683.79
  5170.8 1685.68  5185.0 1684.04  5191.7 1684.12  5205.9 1685.47  5241.3 1686.59
#Mann=3,-1,0
  4773.6    0.05       0  5026.8    0.03       0  5030.8    0.05       0
Bank Sta=5026.8,5030.8
Exp/Cntr=0.3,0.1

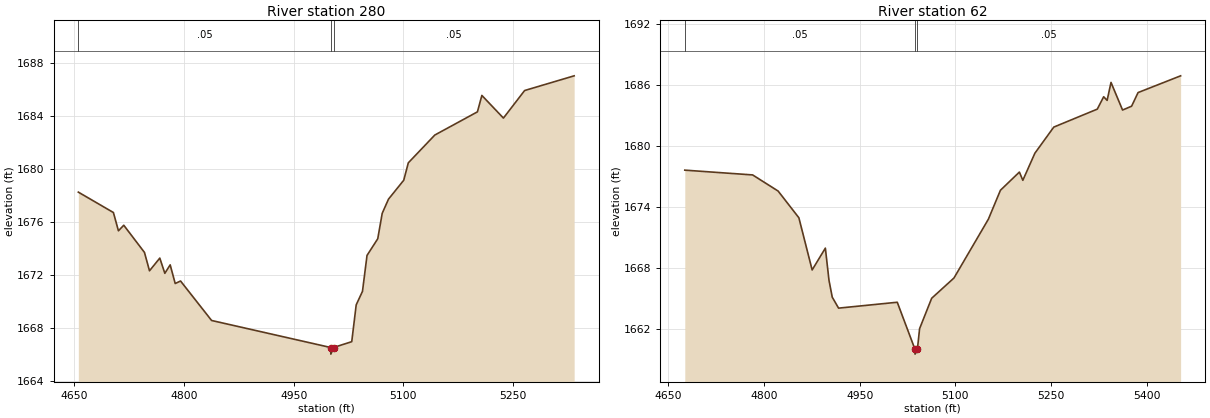
Type RM Length L Ch R = 1,280,218,218,218
BEGIN DESCRIPTION:
Elm 02 42 279.64
END DESCRIPTION:
XS GIS Cut Line= 3
      1604221.29      6869966.65      1603967.37      6870203.65
      1603774.70      6870473.12
#Sta/Elev= 30
  4655.3 1678.23  4703.3 1676.69  4710.2 1675.31  4717.5 1675.73  4745.8 1673.68
  4752.7 1672.29  4766.8 1673.25  4773.7 1672.10  4781.0 1672.74  4787.9 1671.33
  4795.2 1671.52  4837.7 1668.54  5000.6 1666.50  5000.9 1666.00  5004.6 1666.50
  5029.5 1666.94  5035.6 1669.72  5044.2 1670.74  5050.4 1673.45  5065.1 1674.71
  5071.2 1676.63  5079.8 1677.70  5100.7 1679.13  5106.9 1680.44  5143.2 1682.54
  5201.5 1684.29  5207.6 1685.53  5237.1 1683.82  5266.1 1685.90  5333.9 1687.01
#Mann=3,-1,0
  4655.3    0.05       0  5000.6    0.05       0  5004.6    0.05       0
Bank Sta=5000.6,5004.6
Exp/Cntr=0.3,0.1

Type RM Length L Ch R = 1,62,0,0,0
BEGIN DESCRIPTION:
Elm 02 42 472.054
END DESCRIPTION:
XS GIS Cut Line= 3
      1604127.62      6869963.82      1603814.79      6870048.51
      1603647.04      6870469.31
#Sta/Elev= 30
  4675.9 1677.62  4782.2 1677.15  4822.2 1675.56  4854.7 1672.93  4875.5 1667.79
  4896.2 1669.94  4901.9 1666.77  4907.0 1665.11  4916.9 1664.03  5008.9 1664.61
  5036.5 1660.00  5036.8 1659.50  5040.5 1660.00  5043.9 1662.01  5062.8 1665.00
  5097.8 1667.00  5151.7 1672.79  5170.6 1675.64  5200.3 1677.43  5205.7 1676.62
  5224.6 1679.29  5254.2 1681.86  5322.4 1683.63  5332.4 1684.85  5337.8 1684.49
  5343.9 1686.26  5362.0 1683.54  5376.2 1683.92  5386.3 1685.26  5453.0 1686.91
#Mann=3,-1,0
  4675.9    0.05       0  5036.5    0.03       0  5040.5    0.05       0
Bank Sta=5036.5,5040.5
Exp/Cntr=0.3,0.1

Chan Stop Cuts=-1