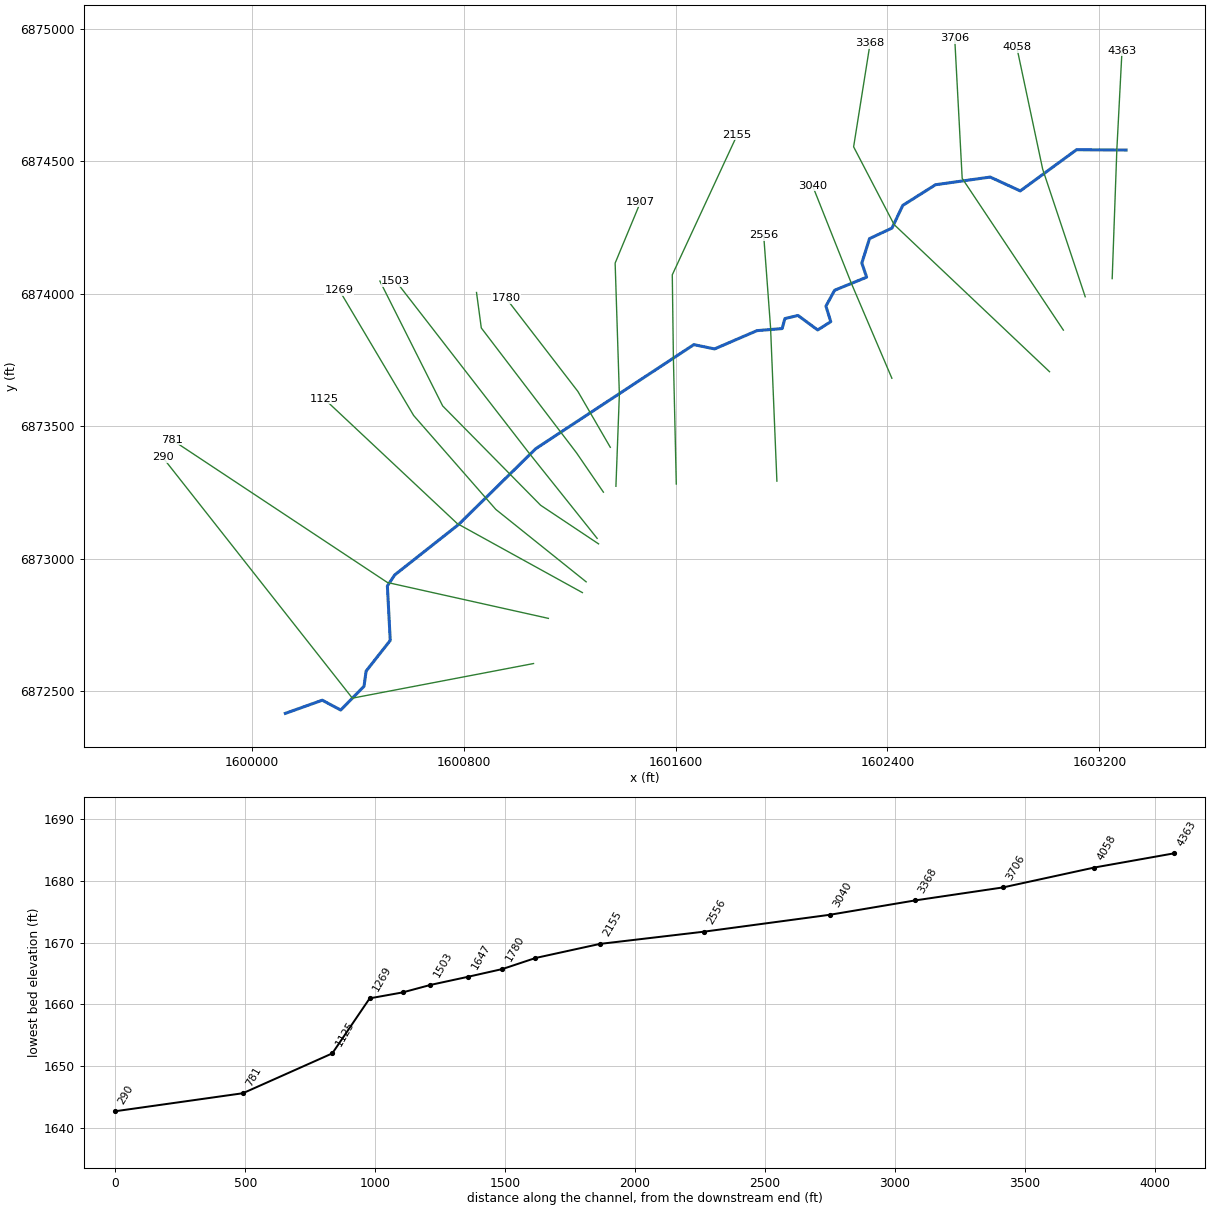
--- Elm 02 43.prj (project) ---

Proj Title=Elm 02 43 Base Level Engineering
Current Plan=p01
Default Exp/Contr=0.3,0.1
English Units
Geom File=g01
Flow File=f01
Plan File=p01
Y Axis Title=Elevation
X Axis Title(PF)=Main Channel Distance
X Axis Title(XS)=Station
BEGIN DESCRIPTION:
Elm 02 43
END DESCRIPTION:
DSS Export Rating Curves= 0
DSS Export Rating Curve Sorted= 0
DSS Export Volume Flow Curves= 0
DXF OffsetX= 0
DXF OffsetY= 0
DXF ScaleX= 1
DXF ScaleY= 10

--- Elm 02 43.p01 (plan) ---

Plan Title=Multiple Run
Short Identifier=Multiple
Geom File=g01
Flow File=f01
Subcritical Flow
K Sum by GR= 0
Std Step Tol= 0.01
Critical Tol= 0.01
Num of Std Step Trials= 20
Max Error Tol= 0.3
Flow Tol Ratio= 0.001
Split Flow NTrial= 30
Split Flow Tol= 0.02
Split Flow Ratio= 0.02
Log Output Level= 0
Friction Slope Method= 1
Unsteady Friction Slope Method= 2
Unsteady Bridges Friction Slope Method= 1
Parabolic Critical Depth
Global Vel Dist=  1 , 1 , 1
Global Log Level= 0
CheckData=True
Encroach Param= -1, 0, 0, 0
BEGIN DESCRIPTION:
Multiple Run
END DESCRIPTION:

--- Elm 02 43.f01 (steady flow) ---

Flow Title=Multiple
Program Version=4.10
Number of Profiles= 7
Profile Names=10-year,25-year,50-year,1pct_min,100-year,1pct_plu,500-year
River Rch & RM=Elm 02 43,Reach-1         ,4363
     117     155     185     137     219     302     313
Boundary for River Rch & Prof#=Elm 02 43,Reach-1         , 1
Up Type= 0
Dn Type= 3
Dn Slope=0.005
Boundary for River Rch & Prof#=Elm 02 43,Reach-1         , 2
Up Type= 0
Dn Type= 3
Dn Slope=0.005
Boundary for River Rch & Prof#=Elm 02 43,Reach-1         , 3
Up Type= 0
Dn Type= 3
Dn Slope=0.005
Boundary for River Rch & Prof#=Elm 02 43,Reach-1         , 4
Up Type= 0
Dn Type= 3
Dn Slope=0.005
Boundary for River Rch & Prof#=Elm 02 43,Reach-1         , 5
Up Type= 0
Dn Type= 3
Dn Slope=0.005
Boundary for River Rch & Prof#=Elm 02 43,Reach-1         , 6
Up Type= 0
Dn Type= 3
Dn Slope=0.005
Boundary for River Rch & Prof#=Elm 02 43,Reach-1         , 7
Up Type= 0
Dn Type= 3
Dn Slope=0.005
DSS Import GetInterval= 0
DSS Import GetPeak= 0
DSS Import FillOption= 0

--- Elm 02 43.g01 (geometry) ---

Geom Title=Existing Conditions

River Reach=Elm 02 43,Reach-1
Reach XY= 30
      1603301.01      6874542.28      1603113.82      6874543.50
      1602901.45      6874387.98      1602787.98      6874440.24
      1602581.46      6874411.35      1602458.00      6874333.43
      1602417.06      6874247.74      1602332.36      6874207.91
      1602303.31      6874115.75      1602321.54      6874062.36
      1602200.44      6874012.88      1602167.89      6873952.99
      1602186.12      6873894.39      1602136.64      6873863.14
      1602062.42      6873917.83      1602012.94      6873906.11
      1602002.53      6873868.35      1601907.47      6873860.54
      1601747.32      6873791.53      1601669.19      6873807.70
      1601072.84      6873415.23      1600781.17      6873128.77
      1600540.16      6872938.46      1600512.34      6872896.72
      1600523.15      6872691.15      1600431.96      6872575.23
      1600424.23      6872518.04      1600336.13      6872428.39
      1600266.58      6872465.49      1600127.22      6872415.78

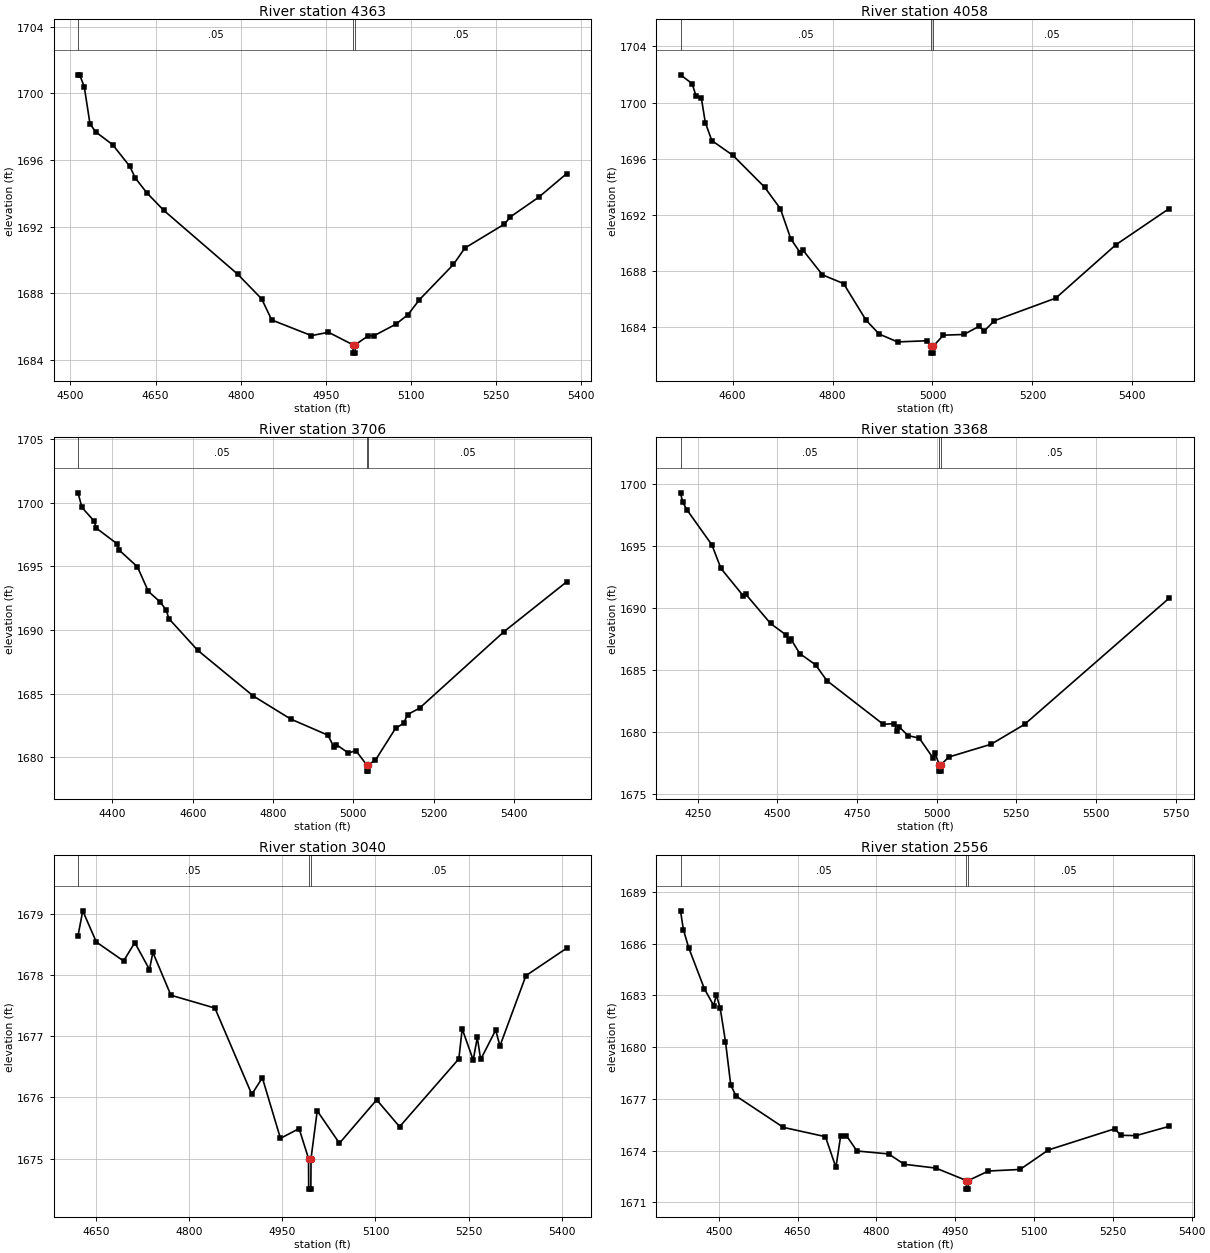
Type RM Length L Ch R = 1,4363,305,305,305
BEGIN DESCRIPTION:
Elm 02 43 4318.095
END DESCRIPTION:
XS GIS Cut Line= 3
      1603248.42      6874056.93      1603265.97      6874543.32
      1603285.46      6874917.31
#Sta/Elev= 30
  4513.3 1701.11  4516.3 1701.11  4524.4 1700.39  4534.4 1698.18  4544.4 1697.69
  4574.4 1696.92  4604.4 1695.63  4614.4 1694.92  4634.4 1694.04  4664.5 1692.98
  4794.5 1689.16  4837.0 1687.67  4854.6 1686.41  4924.6 1685.47  4954.7 1685.67
  4997.8 1684.92  4998.1 1684.42  5001.6 1684.42  5001.8 1684.92  5024.7 1685.46
  5034.7 1685.46  5073.6 1686.16  5094.8 1686.73  5114.8 1687.62  5174.9 1689.74
  5194.9 1690.72  5264.8 1692.16  5275.1 1692.59  5325.1 1693.77  5374.5 1695.19
#Mann=3,-1,0
  4513.3    0.05       0  4997.8   0.035       0  5001.8    0.05       0
Bank Sta=4997.8,5001.8
Exp/Cntr=0.3,0.1

Type RM Length L Ch R = 1,4058,352,352,352
BEGIN DESCRIPTION:
Elm 02 43 4057.81
END DESCRIPTION:
XS GIS Cut Line= 3
      1603146.56      6873988.49      1602985.98      6874470.23
      1602888.33      6874930.28
#Sta/Elev= 30
  4495.8 1701.98  4519.1 1701.35  4526.9 1700.47  4537.4 1700.36  4545.4 1698.58
  4558.5 1697.29  4600.7 1696.24  4663.9 1693.98  4695.6 1692.44  4716.6 1690.28
  4735.2 1689.31  4740.4 1689.50  4779.9 1687.72  4822.1 1687.10  4866.9 1684.50
  4893.3 1683.50  4930.2 1682.94  4988.2 1683.02  4997.8 1682.64  4998.0 1682.14
  5001.5 1682.14  5001.8 1682.64  5021.8 1683.42  5062.7 1683.47  5093.3 1684.05
  5103.5 1683.71  5123.8 1684.45  5246.7 1686.06  5366.9 1689.86  5473.9 1692.45
#Mann=3,-1,0
  4495.8    0.05       0  4997.8    0.05       0  5001.8    0.05       0
Bank Sta=4997.8,5001.8
Exp/Cntr=0.3,0.1

Type RM Length L Ch R = 1,3706,338,338,338
BEGIN DESCRIPTION:
Elm 02 43 3705.69
END DESCRIPTION:
XS GIS Cut Line= 3
      1603064.11      6873862.57      1602682.16      6874435.51
      1602654.00      6874963.98
#Sta/Elev= 30
  4314.1 1700.76  4324.1 1699.61  4354.1 1698.55  4360.1 1697.98  4411.2 1696.77
  4417.2 1696.25  4462.3 1694.95  4489.3 1693.03  4519.4 1692.18  4534.4 1691.53
  4540.4 1690.89  4612.5 1688.40  4750.7 1684.82  4843.9 1683.01  4937.0 1681.74
  4952.0 1680.79  4958.1 1680.99  4988.1 1680.34  5006.4 1680.53  5033.2 1679.42
  5033.5 1678.92  5037.0 1678.92  5037.2 1679.42  5055.2 1679.78  5105.3 1682.28
  5125.3 1682.67  5135.4 1683.36  5165.4 1683.87  5375.7 1689.87  5531.9 1693.78
#Mann=3,-1,0
  4314.1    0.05       0  5033.2   0.035       0  5037.2    0.05       0
Bank Sta=5033.2,5037.2
Exp/Cntr=0.3,0.1

Type RM Length L Ch R = 1,3368,328,328,328
BEGIN DESCRIPTION:
Elm 02 43 3367.68
END DESCRIPTION:
XS GIS Cut Line= 4
      1603011.93      6873705.47      1602425.13      6874261.03
      1602272.35      6874554.43      1602334.56      6874944.94
#Sta/Elev= 30
  4195.9 1699.27  4202.7 1698.52  4216.9 1697.87  4294.5 1695.07  4322.9 1693.17
  4393.6 1690.94  4400.5 1691.10  4478.6 1688.73  4528.0 1687.79  4535.2 1687.34
  4542.1 1687.48  4570.4 1686.30  4619.8 1685.40  4655.4 1684.12  4832.2 1680.60
  4867.4 1680.65  4874.6 1680.05  4881.5 1680.41  4909.8 1679.69  4945.4 1679.48
  4987.9 1677.91  4994.8 1678.26  5008.6 1677.32  5008.9 1676.82  5012.4 1676.82
  5012.6 1677.32  5038.4 1677.96  5171.0 1678.99  5275.8 1680.59  5730.2 1690.78
#Mann=3,-1,0
  4195.9    0.05       0  5008.6   0.035       0  5012.6    0.05       0
Bank Sta=5008.6,5012.6
Exp/Cntr=0.3,0.1

Type RM Length L Ch R = 1,3040,484,484,484
BEGIN DESCRIPTION:
Elm 02 43 3040.2
END DESCRIPTION:
XS GIS Cut Line= 3
      1602416.73      6873680.89      1602264.83      6874036.78
      1602117.26      6874407.86
#Sta/Elev= 30
  4621.4 1678.64  4629.1 1679.05  4650.9 1678.54  4694.7 1678.23  4712.8 1678.53
  4736.4 1678.09  4741.9 1678.37  4770.9 1677.67  4841.7 1677.46  4901.0 1676.05
  4918.0 1676.32  4947.1 1675.33  4977.1 1675.49  4992.3 1675.00  4992.5 1674.50
  4996.0 1674.50  4996.3 1675.00  5006.3 1675.78  5042.0 1675.25  5101.9 1675.96
  5138.8 1675.52  5234.1 1676.63  5239.5 1677.12  5257.2 1676.61  5263.8 1676.98
  5269.2 1676.62  5293.4 1677.10  5300.2 1676.84  5342.0 1677.99  5407.7 1678.44
#Mann=3,-1,0
  4621.4    0.05       0  4992.3   0.035       0  4996.3    0.05       0
Bank Sta=4992.3,4996.3
Exp/Cntr=0.3,0.1

Type RM Length L Ch R = 1,2556,401,401,401
BEGIN DESCRIPTION:
Elm 02 43 2555.55
END DESCRIPTION:
XS GIS Cut Line= 3
      1601982.71      6873292.47      1601958.84      6873871.85
      1601932.80      6874221.21
#Sta/Elev= 30
  4427.2 1687.90  4432.7 1686.81  4442.7 1685.77  4472.8 1683.37  4490.4 1682.41
  4495.4 1683.03  4502.8 1682.25  4512.8 1680.32  4522.8 1677.81  4532.8 1677.17
  4622.9 1675.35  4703.0 1674.81  4723.0 1673.03  4731.9 1674.84  4743.0 1674.87
  4763.0 1673.98  4823.1 1673.81  4853.1 1673.21  4913.1 1672.99  4971.2 1672.27
  4971.4 1671.77  4974.9 1671.77  4975.2 1672.27  5013.2 1672.82  5073.4 1672.91
  5127.3 1674.04  5253.9 1675.27  5264.7 1674.89  5294.0 1674.87  5357.4 1675.41
#Mann=3,-1,0
  4427.2    0.05       0  4971.2   0.035       0  4975.2    0.05       0
Bank Sta=4971.2,4975.2
Exp/Cntr=0.3,0.1

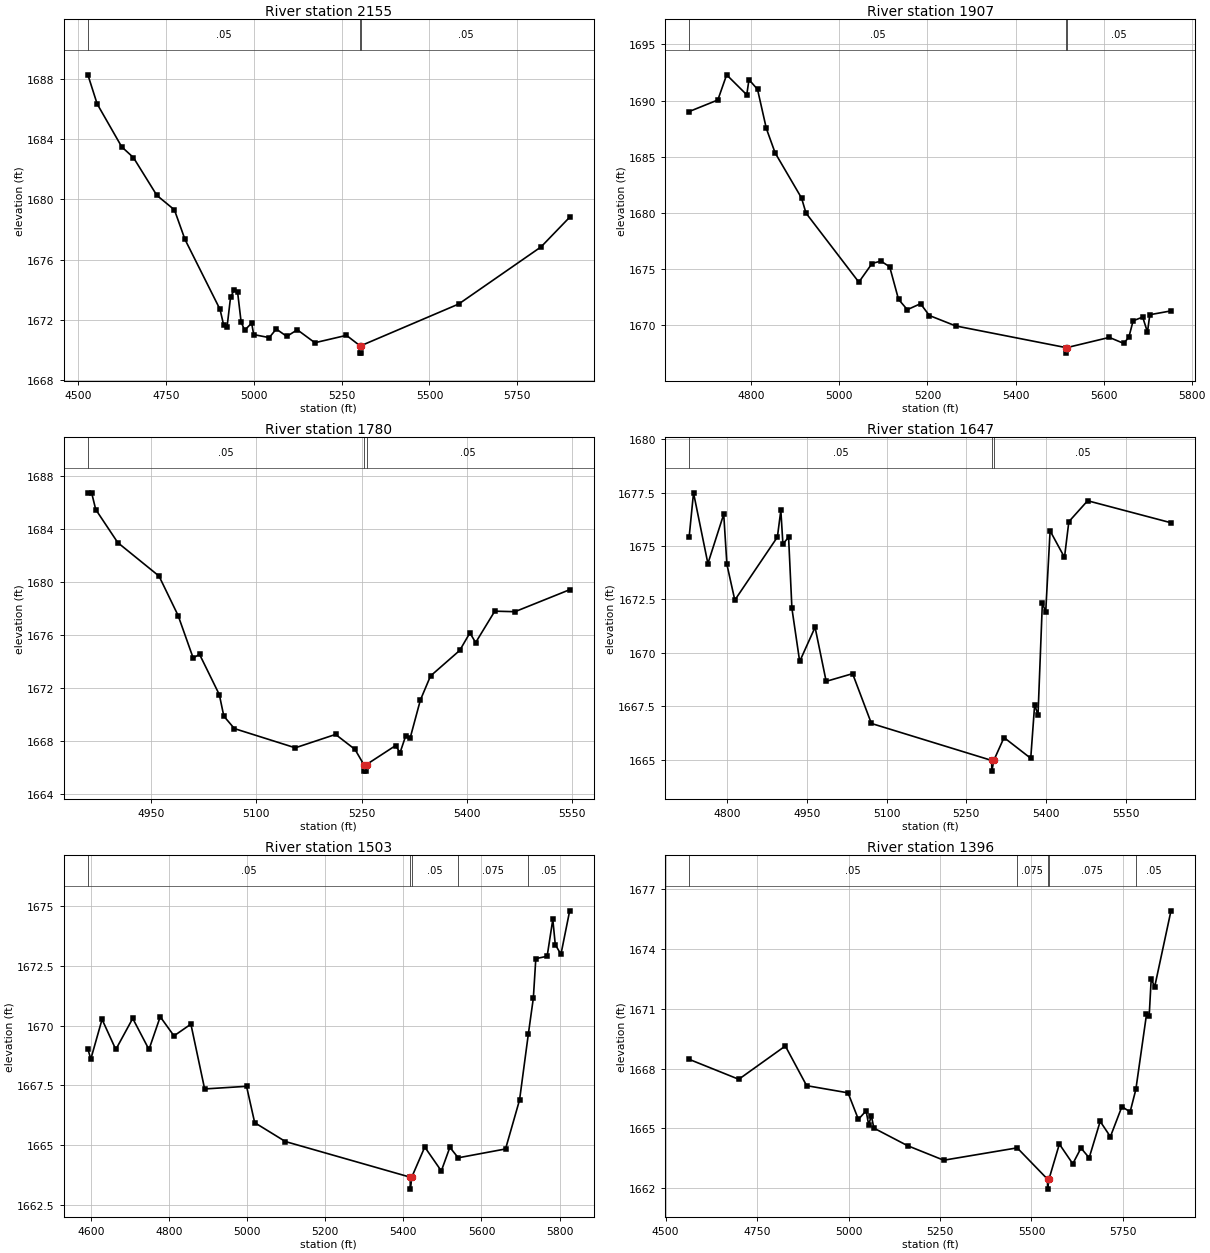
Type RM Length L Ch R = 1,2155,248,248,248
BEGIN DESCRIPTION:
Elm 02 43 2154.59
END DESCRIPTION:
XS GIS Cut Line= 4
      1601602.94      6873281.58      1601592.08      6873754.66
      1601587.81      6874071.18      1601833.00      6874599.83
#Sta/Elev= 30
  4526.9 1688.26  4553.3 1686.33  4623.3 1683.48  4656.6 1682.77  4723.4 1680.26
  4773.4 1679.30  4803.4 1677.34  4903.4 1672.69  4913.4 1671.68  4923.4 1671.53
  4933.4 1673.51  4943.4 1673.96  4953.4 1673.84  4963.4 1671.86  4973.4 1671.31
  4993.4 1671.78  4999.3 1671.02  5043.5 1670.82  5063.5 1671.39  5093.5 1670.90
  5123.5 1671.34  5173.5 1670.48  5263.5 1670.97  5301.5 1670.29  5301.7 1669.79
  5305.2 1669.79  5305.5 1670.29  5583.3 1673.05  5817.8 1676.84  5899.4 1678.81
#Mann=3,-1,0
  4526.9    0.05       0  5301.5    0.05       0  5305.5    0.05       0
Bank Sta=5301.5,5305.5
Exp/Cntr=0.3,0.1

Type RM Length L Ch R = 1,1907,127,127,127
BEGIN DESCRIPTION:
Elm 02 43 1906.55
END DESCRIPTION:
XS GIS Cut Line= 4
      1601375.07      6873272.93      1601388.09      6873620.11
      1601372.11      6874115.57      1601468.45      6874347.30
#Sta/Elev= 30
  4658.9 1689.02  4724.0 1690.05  4744.0 1692.29  4789.7 1690.51  4794.7 1691.86
  4814.1 1691.00  4834.1 1687.52  4854.1 1685.34  4914.1 1681.32  4924.2 1679.98
  5044.2 1673.83  5074.2 1675.49  5094.3 1675.71  5114.3 1675.19  5134.3 1672.30
  5154.3 1671.38  5184.3 1671.91  5204.3 1670.86  5264.3 1669.93  5513.5 1668.01
  5513.8 1667.51  5517.5 1668.01  5613.0 1668.91  5645.5 1668.38  5657.3 1668.92
  5667.1 1670.39  5688.8 1670.72  5699.6 1669.38  5705.0 1670.93  5753.0 1671.27
#Mann=3,-1,0
  4658.9    0.05       0  5513.5    0.05       0  5517.5    0.05       0
Bank Sta=5513.5,5517.5
Exp/Cntr=0.3,0.1

Type RM Length L Ch R = 1,1780,133,133,133
BEGIN DESCRIPTION:
Mapping XS 0b320f7f
END DESCRIPTION:
XS GIS Cut Line= 3
      1601353.82      6873420.21      1601231.45      6873631.11
      1600960.63      6873982.66
#Sta/Elev= 30
  4859.5 1686.73  4864.9 1686.72  4870.7 1685.47  4902.2 1682.97  4961.0 1680.45
  4988.3 1677.47  5009.8 1674.26  5018.8 1674.55  5047.1 1671.50  5053.5 1669.88
  5068.6 1668.94  5155.5 1667.49  5213.0 1668.50  5240.7 1667.37  5253.2 1666.23
  5253.4 1665.73  5256.9 1665.73  5257.2 1666.23  5298.7 1667.66  5305.0 1667.12
  5313.2 1668.41  5319.5 1668.24  5334.0 1671.09  5348.5 1672.91  5390.2 1674.84
  5404.7 1676.16  5412.9 1675.43  5440.2 1677.80  5469.0 1677.76  5547.1 1679.42
#Mann=3,-1,0
  4859.5    0.05       0  5253.2    0.05       0  5257.2    0.05       0
Bank Sta=5253.2,5257.2
Exp/Cntr=0.3,0.1

Type RM Length L Ch R = 1,1647,144,144,144
BEGIN DESCRIPTION:
Mapping XS 97c51c8c
END DESCRIPTION:
XS GIS Cut Line= 4
      1601327.83      6873250.87      1601226.24      6873399.34
      1600866.87      6873870.70      1600848.85      6874004.56
#Sta/Elev= 30
  4727.8 1675.43  4736.0 1677.49  4763.1 1674.18  4792.9 1676.49  4798.9 1674.14
  4813.8 1672.47  4894.0 1675.42  4900.5 1676.67  4904.4 1675.10  4915.1 1675.41
  4921.4 1672.08  4936.0 1669.60  4965.0 1671.20  4985.9 1668.67  5035.7 1669.03
  5071.1 1666.70  5297.7 1664.97  5298.0 1664.47  5301.7 1664.97  5321.0 1666.04
  5371.3 1665.07  5378.7 1667.58  5385.0 1667.09  5393.2 1672.33  5399.5 1671.92
  5407.8 1675.71  5434.9 1674.47  5443.1 1676.14  5478.5 1677.12  5635.5 1676.09
#Mann=3,-1,0
  4727.8    0.05       0  5297.7    0.03       0  5301.7    0.05       0
Bank Sta=5297.7,5301.7
Exp/Cntr=0.3,0.1

Type RM Length L Ch R = 1,1503,107,107,107
BEGIN DESCRIPTION:
Elm 02 43 1503.44
END DESCRIPTION:
XS GIS Cut Line= 3
      1601304.12      6873076.49      1601043.68      6873402.91
      1600543.96      6874047.76
#Sta/Elev= 30
  4592.4 1669.02  4599.9 1668.60  4628.7 1670.26  4663.9 1669.00  4707.2 1670.30
  4748.8 1669.00  4777.6 1670.37  4812.8 1669.57  4856.1 1670.06  4891.3 1667.35
  4998.6 1667.46  5019.4 1665.94  5098.1 1665.15  5417.5 1663.66  5417.8 1663.16
  5421.5 1663.66  5454.8 1664.92  5497.2 1663.92  5519.1 1664.91  5540.4 1664.47
  5661.6 1664.84  5697.5 1666.89  5720.1 1669.66  5732.8 1671.15  5739.1 1672.80
  5768.1 1672.90  5782.6 1674.44  5788.9 1673.39  5803.4 1672.98  5825.8 1674.80
#Mann=5,-1,0
  4592.4    0.05       0  5417.5    0.05       0  5421.5    0.05       0
  5540.4   0.075       0  5720.1    0.05       0
Bank Sta=5417.5,5421.5
Exp/Cntr=0.3,0.1

Type RM Length L Ch R = 1,1396,127,127,127
BEGIN DESCRIPTION:
Mapping XS 96a0cb9c
END DESCRIPTION:
XS GIS Cut Line= 4
      1601309.54      6873055.62      1601090.82      6873201.43
      1600721.03      6873576.43      1600484.05      6874047.79
#Sta/Elev= 30
  4564.3 1668.46  4699.9 1667.46  4827.2 1669.13  4885.4 1667.14  4998.6 1666.78
  5026.9 1665.45  5048.0 1665.88  5055.1 1665.17  5062.2 1665.64  5069.3 1665.01
  5161.2 1664.13  5260.2 1663.40  5461.0 1664.02  5543.9 1662.45  5544.1 1661.95
  5547.9 1662.45  5576.3 1664.21  5613.0 1663.22  5635.4 1664.01  5657.8 1663.52
  5687.9 1665.35  5715.8 1664.58  5747.3 1666.09  5769.7 1665.82  5785.4 1666.95
  5814.5 1670.71  5821.9 1670.65  5827.4 1672.50  5836.9 1672.10  5881.4 1675.91
#Mann=5,-1,0
  4564.3    0.05       0  5461.0   0.075       0  5543.9    0.05       0
  5547.9   0.075       0  5785.4    0.05       0
Bank Sta=5543.9,5547.9
Exp/Cntr=0.3,0.1

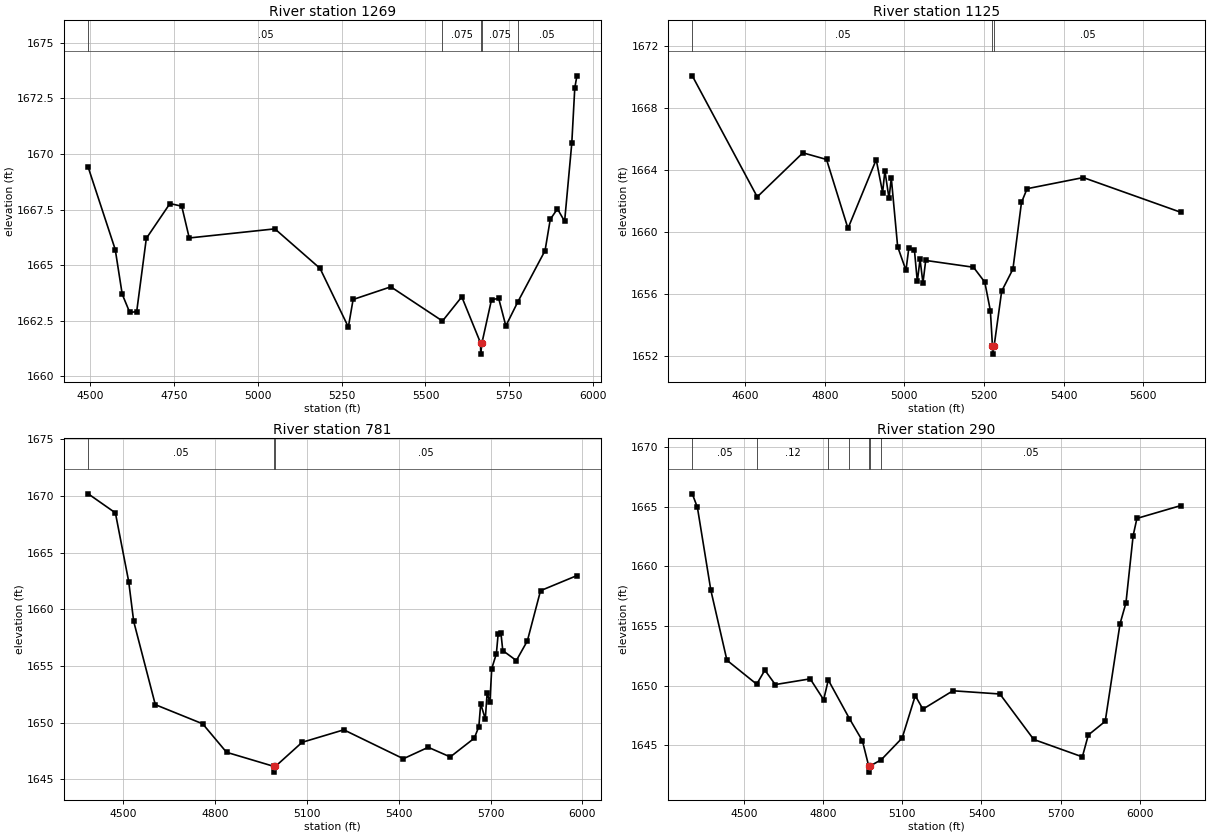
Type RM Length L Ch R = 1,1269,144,144,144
BEGIN DESCRIPTION:
Mapping XS a6e60b7d
END DESCRIPTION:
XS GIS Cut Line= 4
      1601262.67      6872912.39      1600921.55      6873185.80
      1600611.66      6873539.97      1600330.66      6874013.50
#Sta/Elev= 30
  4493.5 1669.40  4574.1 1665.70  4594.9 1663.69  4617.3 1662.87  4638.1 1662.90
  4666.9 1666.20  4737.4 1667.77  4772.6 1667.65  4795.0 1666.22  5050.5 1666.63
  5185.3 1664.85  5269.8 1662.21  5284.0 1663.45  5396.6 1664.02  5550.7 1662.48
  5608.3 1663.57  5664.4 1661.49  5664.7 1660.99  5668.4 1661.49  5697.0 1663.44
  5718.4 1663.50  5739.8 1662.26  5774.8 1663.32  5856.8 1665.65  5872.4 1667.06
  5893.8 1667.53  5915.2 1666.97  5936.6 1670.49  5945.5 1672.97  5951.9 1673.52
#Mann=5,-1,0
  4493.5    0.05       0  5550.7   0.075       0  5664.4    0.03       0
  5668.4   0.075       0  5774.8    0.05       0
Bank Sta=5664.4,5668.4
Exp/Cntr=0.3,0.1

Type RM Length L Ch R = 1,1125,344,344,344
BEGIN DESCRIPTION:
Elm 02 43 1124.79
END DESCRIPTION:
XS GIS Cut Line= 3
      1601248.54      6872871.66      1600776.32      6873132.08
      1600273.53      6873603.66
#Sta/Elev= 30
  4466.7 1670.09  4630.0 1662.26  4744.8 1665.11  4804.2 1664.68  4858.1 1660.22
  4929.1 1664.67  4945.2 1662.54  4950.9 1663.95  4961.3 1662.16  4967.0 1663.48
  4983.0 1659.04  5003.9 1657.51  5011.0 1658.94  5025.1 1658.84  5032.4 1656.79
  5039.3 1658.22  5046.6 1656.69  5053.5 1658.15  5173.6 1657.71  5202.0 1656.75
  5216.1 1654.90  5221.4 1652.59  5221.7 1652.09  5225.4 1652.59  5244.5 1656.16
  5272.8 1657.59  5294.3 1661.90  5308.4 1662.79  5449.6 1663.51  5695.3 1661.26
#Mann=3,-1,0
  4466.7    0.05       0  5221.4    0.03       0  5225.4    0.05       0
Bank Sta=5221.4,5225.4
Exp/Cntr=0.3,0.1

Type RM Length L Ch R = 1,781,491,491,491
BEGIN DESCRIPTION:
Elm 02 43 780.73
END DESCRIPTION:
XS GIS Cut Line= 3
      1601120.05      6872774.44      1600512.43      6872909.86
      1599699.94      6873448.05
#Sta/Elev= 30
  4385.2 1670.19  4474.0 1668.51  4517.5 1662.45  4533.8 1658.94  4604.4 1651.60
  4759.2 1649.91  4837.2 1647.40  4992.8 1646.15  4993.1 1645.65  4996.8 1646.15
  5084.2 1648.28  5220.5 1649.38  5415.1 1646.83  5496.4 1647.84  5568.4 1646.99
  5646.8 1648.64  5661.8 1649.66  5667.8 1651.68  5682.9 1650.33  5688.9 1652.63
  5697.9 1651.80  5703.9 1654.78  5719.0 1656.08  5725.0 1657.87  5734.0 1657.91
  5740.0 1656.37  5784.3 1655.49  5820.3 1657.22  5863.4 1661.65  5982.3 1662.98
#Mann=3,-1,0
  4385.2    0.05       0  4992.8    0.03       0  4996.8    0.05       0
Bank Sta=4992.8,4996.8
Exp/Cntr=0.3,0.1

Type RM Length L Ch R = 1,290,0,0,0
BEGIN DESCRIPTION:
Elm 02 43 557.68
END DESCRIPTION:
XS GIS Cut Line= 3
      1601064.01      6872603.90      1600380.18      6872473.21
      1599664.72      6873381.72
#Sta/Elev= 30
  4303.8 1666.07  4323.2 1664.93  4374.1 1657.99  4435.1 1652.12  4548.0 1650.11
  4578.9 1651.29  4618.4 1650.08  4750.8 1650.56  4801.7 1648.81  4819.4 1650.46
  4899.4 1647.23  4948.6 1645.37  4972.7 1643.24  4973.0 1642.74  4976.7 1643.24
  5020.2 1643.78  5099.4 1645.60  5149.1 1649.15  5178.0 1648.02  5291.9 1649.56
  5469.9 1649.29  5598.1 1645.48  5782.5 1644.02  5805.0 1645.85  5869.2 1647.00
  5925.3 1655.17  5947.8 1656.93  5975.0 1662.56  5989.4 1664.01  6156.4 1665.09
#Mann=7,-1,0
  4303.8    0.05       0  4548.0    0.12       0  4819.4    0.05       0
  4899.4    0.12       0  4972.7    0.07       0  4976.7    0.12       0
  5020.2    0.05       0
Bank Sta=4972.7,4976.7
Exp/Cntr=0.3,0.1

Chan Stop Cuts=-1