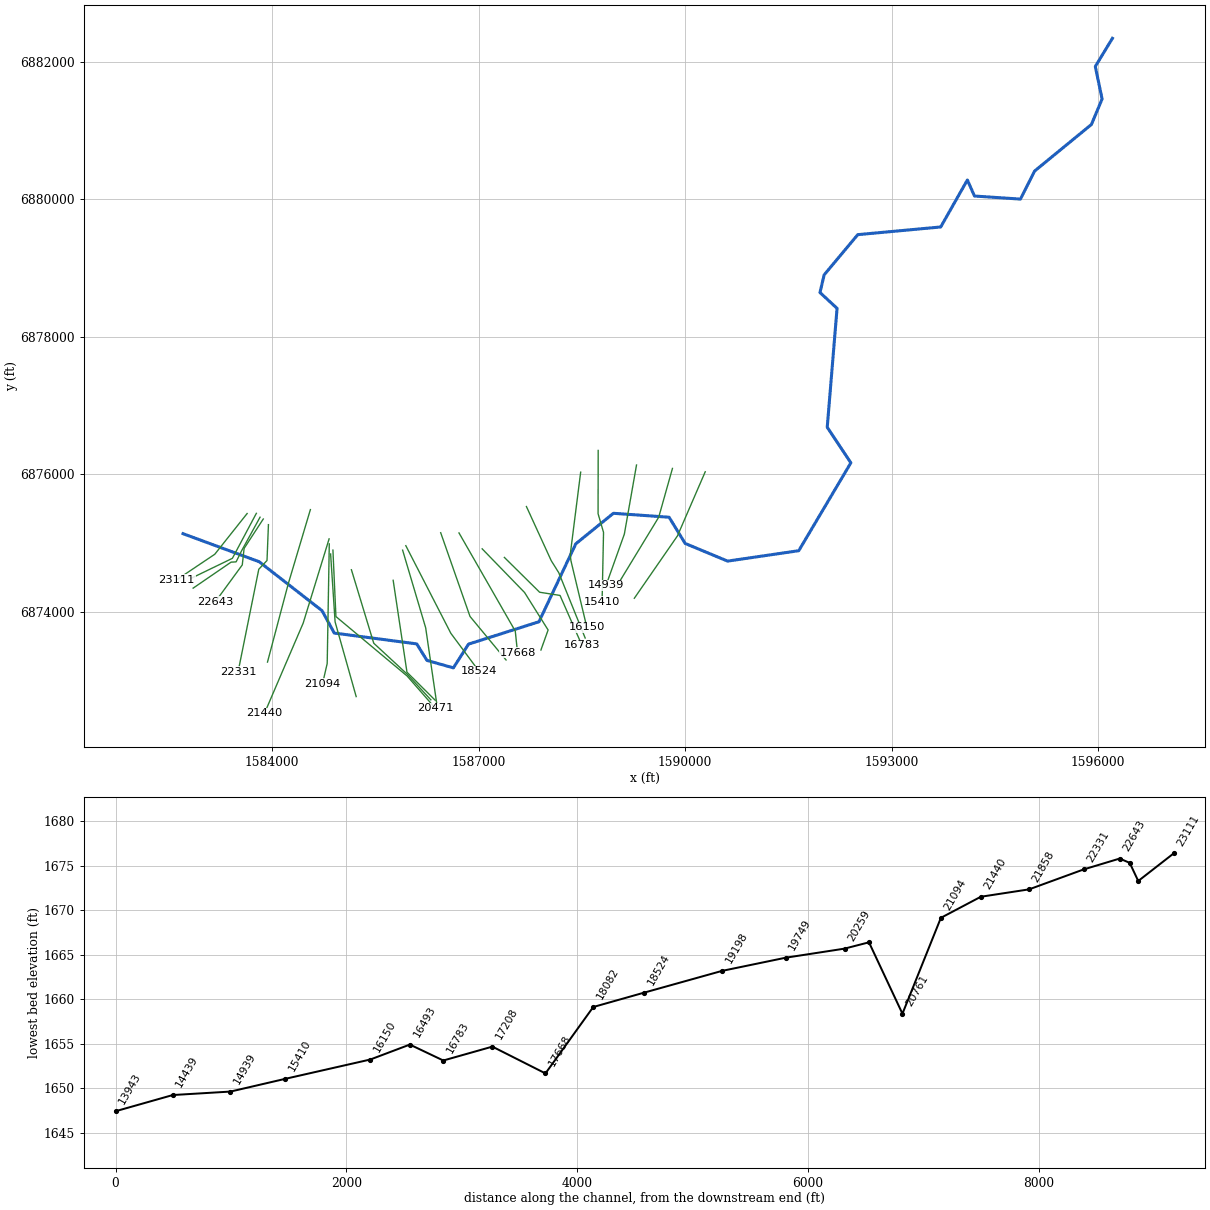
--- Elm 02 44.prj (project) ---

Proj Title=Elm 02 44 Base Level Engineering
Current Plan=p01
Default Exp/Contr=0.3,0.1
English Units
Geom File=g01
Flow File=f01
Plan File=p01
Y Axis Title=Elevation
X Axis Title(PF)=Main Channel Distance
X Axis Title(XS)=Station
BEGIN DESCRIPTION:
Elm 02 44
END DESCRIPTION:
DSS Export Rating Curves= 0
DSS Export Rating Curve Sorted= 0
DSS Export Volume Flow Curves= 0
DXF OffsetX= 0
DXF OffsetY= 0
DXF ScaleX= 1
DXF ScaleY= 10

--- Elm 02 44.p01 (plan) ---

Plan Title=Multiple Run
Program Version=4.10
Short Identifier=Multiple
Geom File=g01
Flow File=f01
Subcritical Flow
K Sum by GR= 0
Std Step Tol= 0.01
Critical Tol= 0.01
Num of Std Step Trials= 20
Max Error Tol= 0.3
Flow Tol Ratio= 0.001
Split Flow NTrial= 30
Split Flow Tol= 0.02
Split Flow Ratio= 0.02
Log Output Level= 0
Friction Slope Method= 1
Unsteady Friction Slope Method= 2
Unsteady Bridges Friction Slope Method= 1
Parabolic Critical Depth
Global Vel Dist= 1 , 1 , 1
Global Log Level= 0
CheckData=True
Encroach Param=-1 ,0,0, 0
BEGIN DESCRIPTION:
Multiple Run
END DESCRIPTION:
Computation Interval=1HOUR
Output Interval=1HOUR
Run HTab= 0
Run UNet= 0
Run PostProcess= 0
Run WQNet= 0
UNET Theta= 1
UNET Theta Warmup= 1
UNET ZTol= 0.02
UNET ZSATol= 0.05
UNET MxIter= 20
UNET MaxInSteps= 0
UNET DtIC= 0
UNET DtMin= 0
UNET MaxCRTS= 20
UNET WFStab= 2
UNET SFStab= 1
UNET WFX= 1
UNET SFX= 1
UNET DSS MLevel= 4
UNET DZMax Abort= 100
UNET Convert EG Bridges= 0
UNET Use Existing IB Tables=-1
UNET Froude Reduction=False
UNET Froude Limit= 1
UNET Froude Power= 10
UNET Time Slicing=0,0, 5
UNET Junction Losses=0
Instantaneous Interval=1HOUR
Write IC File= 0
Write IC File at Sim End=0
Echo Input=False
Echo Parameters=False
Echo Output=False
Write Detailed= 0
WQ AD Non Conservative
WQ ULTIMATE=-1
WQ Max Comp Step=1HOUR
WQ Output Interval=15MIN
WQ Output Selected Increments= 0
WQ Output face flow=0
WQ Output face velocity=0
WQ Output face area=0
WQ Output face dispersion=0
WQ Output cell volume=0
WQ Output cell surface area=0
WQ Output cell continuity=0
WQ Output cumulative cell continuity=0
WQ Output face conc=0
WQ Output face dconc_dx=0
WQ Output face courant=0
WQ Output face peclet=0
WQ Output face adv mass=0
WQ Output face disp mass=0
WQ Output cell mass=0
WQ Output cell source sink temp=0
WQ Output cell source sink nsm=0
WQ Output MaxMinRange=-1
WQ Daily Max Min Mean=-1
WQ Daily Range=0
WQ Daily Time=0
WQ Create Restart=0
WQ Fixed Restart=0
WQ System Summary=0
WQ Use Fixed Temperature=0
Sorting and Armoring Iterations= 10
XS Update Threshold= 0.02
Hydraulics Update Threshold= 0.02
Energy Slope Method= 1
Volume Change Method= 0
XS Weighting Method= 0
Number of US Weighted Cross Sections= 1
Number of DS Weighted Cross Sections= 1
Upstream XS Weight=0.25
Main XS Weight=0.5
Downstream XS Weight=0.25
Number of DS XS's Weighted with US Boundary= 1
Upstream Boundary Weight= 1
Weight of XSs Associated with US Boundary= 0
Number of US XS's Weighted with DS Boundary= 1
Downstream Boundary Weight= 0.5
Weight of XSs Associated with DS Boundary= 0.5
Sediment Output Level= 4
Mass or Volume Output= 0
Output Increment Type= 1
Profile and TS Output Increment= 10
XS Output Flag= 0
XS Output Increment= 10
Disregard all LS=0
Disregard all Conn=0
Disregard all Breaches=0
Disregard all Pumps=0

--- Elm 02 44.f01 (steady flow) ---

Flow Title=Multiple
Program Version=4.10
Number of Profiles= 7
Profile Names=10-year,25-year,50-year,1pct_min,100-year,1pct_plu,500-year
River Rch & RM=Elm 02 44,Reach-1         ,23111
     272     378     466     286     571    1139     867
River Rch & RM=Elm 02 44,Reach-1         ,22331
     331     463     572     352     701    1399    1070
River Rch & RM=Elm 02 44,Reach-1         ,16150
     401     561     693     426     849    1695    1293
Boundary for River Rch & Prof#=Elm 02 44,Reach-1         , 1
Up Type= 0
Dn Type= 3
Dn Slope=0.008
Boundary for River Rch & Prof#=Elm 02 44,Reach-1         , 2
Up Type= 0
Dn Type= 3
Dn Slope=0.008
Boundary for River Rch & Prof#=Elm 02 44,Reach-1         , 3
Up Type= 0
Dn Type= 3
Dn Slope=0.008
Boundary for River Rch & Prof#=Elm 02 44,Reach-1         , 4
Up Type= 0
Dn Type= 3
Dn Slope=0.008
Boundary for River Rch & Prof#=Elm 02 44,Reach-1         , 5
Up Type= 0
Dn Type= 3
Dn Slope=0.008
Boundary for River Rch & Prof#=Elm 02 44,Reach-1         , 6
Up Type= 0
Dn Type= 3
Dn Slope=0.008
Boundary for River Rch & Prof#=Elm 02 44,Reach-1         , 7
Up Type= 0
Dn Type= 3
Dn Slope=0.008
DSS Import GetInterval= 0
DSS Import GetPeak= 0
DSS Import FillOption= 0

--- Elm 02 44.g01 (geometry) ---

Geom Title=Existing Conditions

River Reach=Elm 02 44,Reach-1
Reach XY= 30
      1582705.00      6875138.00      1583811.19      6874730.19
      1584725.09      6874018.21      1584902.29      6873693.40
      1586099.74      6873535.91      1586248.52      6873295.69
      1586632.30      6873187.40      1586852.30      6873532.64
      1587875.17      6873857.60      1588410.36      6874990.70
      1588956.52      6875434.26      1589765.43      6875377.04
      1589998.83      6874995.86      1590615.50      6874739.20
      1591648.97      6874890.50      1592405.70      6876167.85
      1592062.60      6876684.65      1592205.21      6878413.09
      1591956.92      6878643.62      1592018.57      6878901.23
      1592506.46      6879484.46      1593711.08      6879596.13
      1594098.22      6880279.24      1594201.30      6880045.70
      1594869.11      6880001.37      1595074.47      6880408.54
      1595899.88      6881085.71      1596055.24      6881456.46
      1595956.25      6881928.30      1596205.00      6882338.00

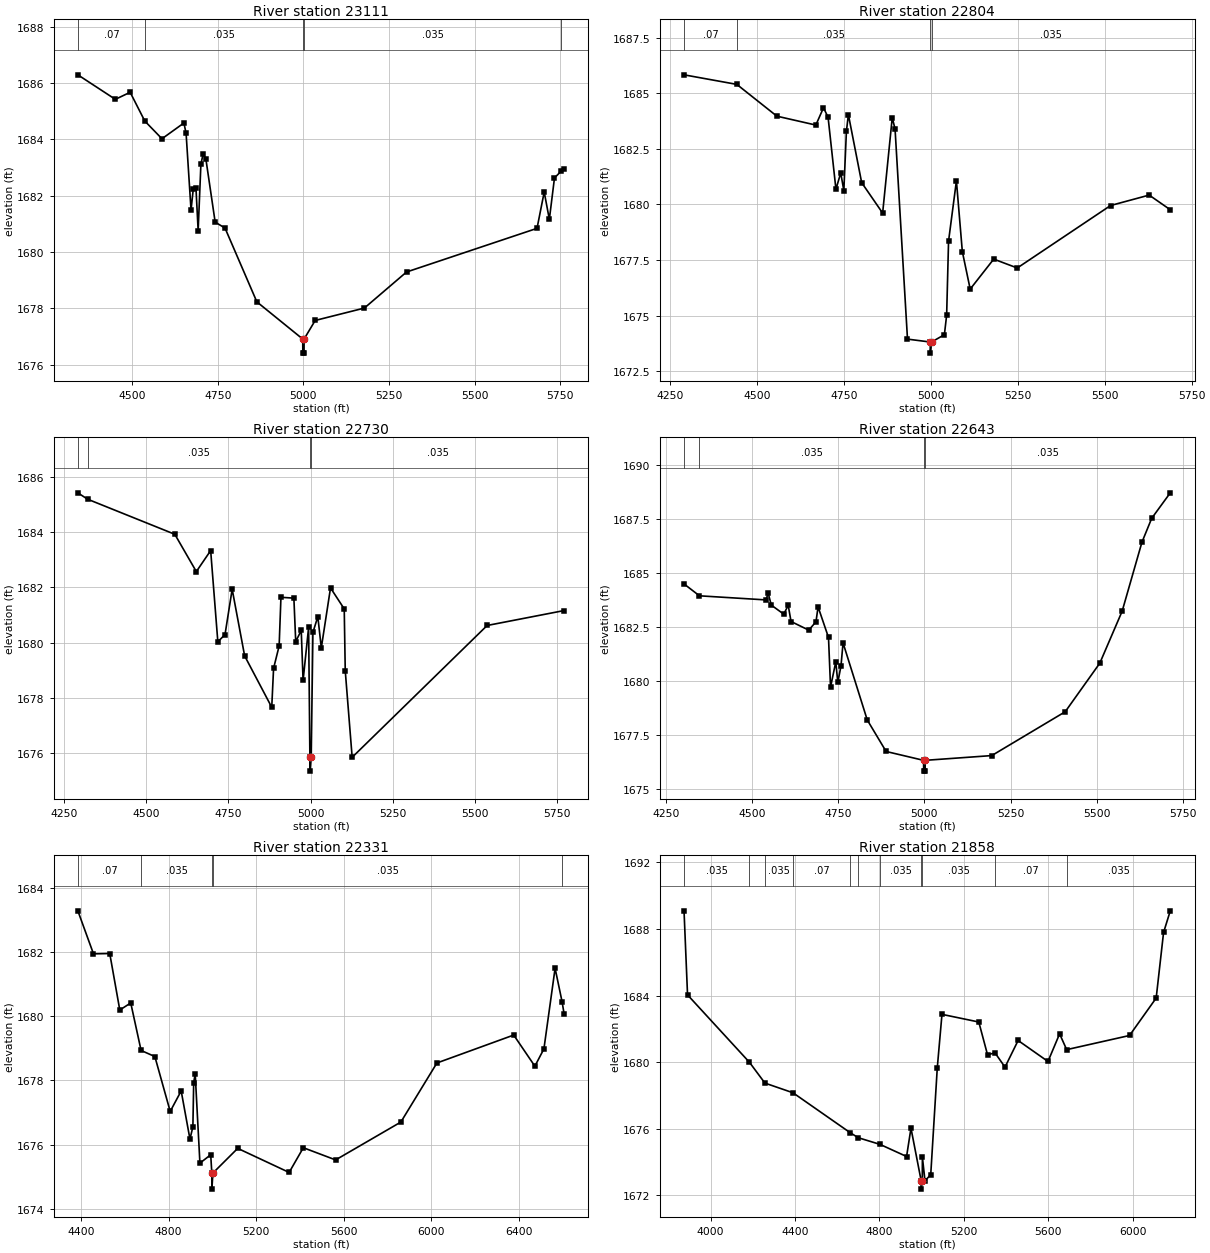
Type RM Length L Ch R = 1,23111,307,307,307
BEGIN DESCRIPTION:
Elm 02 44 35.0
END DESCRIPTION:
XS GIS Cut Line= 3
      1583636.25      6875431.04      1583165.70      6874838.27
      1582614.54      6874468.74
#Sta/Elev= 30
  4341.1 1686.29  4450.6 1685.42  4493.9 1685.67  4536.6 1684.65  4586.8 1684.02
  4650.9 1684.58  4657.3 1684.21  4671.7 1681.49  4678.1 1682.22  4686.1 1682.28
  4692.5 1680.76  4700.5 1683.11  4706.9 1683.48  4715.0 1683.31  4742.2 1681.06
  4771.0 1680.85  4864.0 1678.23  4998.0 1676.91  4998.3 1676.41  5001.8 1676.41
  5002.0 1676.91  5034.4 1677.57  5178.1 1678.01  5301.2 1679.29  5682.4 1680.84
  5703.4 1682.13  5718.4 1681.16  5733.4 1682.63  5752.1 1682.86  5761.5 1682.95
#Mann=5,-1,0
  4341.1    0.07       0  4536.6   0.035       0  4998.0   0.035       0
  5002.0   0.035       0  5752.1   0.063       0
Bank Sta=4998,5002
Exp/Cntr=0.3,0.1

Type RM Length L Ch R = 1,22804,74,74,74
BEGIN DESCRIPTION:
Elm 02 44 34.0
END DESCRIPTION:
XS GIS Cut Line= 3
      1583770.25      6875433.69      1583422.11      6874779.66
      1582830.41      6874492.77
#Sta/Elev= 30
  4290.0 1685.83  4441.8 1685.40  4557.0 1683.97  4669.1 1683.57  4691.1 1684.35
  4704.3 1683.92  4726.9 1680.68  4740.7 1681.42  4749.6 1680.62  4757.0 1683.29
  4762.7 1684.04  4800.9 1680.98  4861.2 1679.61  4888.8 1683.90  4896.9 1683.40
  4932.7 1673.94  4998.0 1673.81  4998.3 1673.31  5002.0 1673.81  5038.8 1674.14
  5045.3 1675.02  5050.8 1678.35  5073.4 1681.06  5090.4 1677.88  5113.0 1676.19
  5180.7 1677.54  5248.4 1677.14  5516.7 1679.95  5627.8 1680.42  5688.5 1679.76
#Mann=4,-1,0
  4290.0    0.07       0  4441.8   0.035       0  4998.0   0.035       0
  5002.0   0.035       0
Bank Sta=4998,5002
Exp/Cntr=0.3,0.1

Type RM Length L Ch R = 1,22730,87,87,87
BEGIN DESCRIPTION:
Elm 02 44 33.3
END DESCRIPTION:
XS GIS Cut Line= 5
      1583823.93      6875377.55      1583553.72      6874884.94
      1583475.81      6874727.73      1583403.34      6874724.32
      1582852.01      6874346.18
#Sta/Elev= 30
  4292.5 1685.42  4322.0 1685.19  4587.3 1683.92  4652.7 1682.57  4696.3 1683.33
  4718.1 1680.03  4739.9 1680.29  4761.7 1681.93  4799.6 1679.52  4882.0 1677.66
  4887.6 1679.07  4904.5 1679.88  4910.0 1681.64  4949.3 1681.61  4954.9 1680.04
  4971.7 1680.44  4977.3 1678.63  4994.1 1680.55  4998.0 1675.85  4998.3 1675.35
  5002.0 1675.85  5007.2 1680.37  5022.1 1680.94  5032.7 1679.81  5060.7 1681.98
  5102.4 1681.22  5105.5 1678.98  5126.5 1675.85  5536.9 1680.62  5770.9 1681.16
#Mann=4,-1,0
  4292.5    0.07       0  4322.0   0.035       0  4998.0   0.035       0
  5002.0   0.035       0
Bank Sta=4998,5002
Exp/Cntr=0.3,0.1

Type RM Length L Ch R = 1,22643,312,312,312
BEGIN DESCRIPTION:
Elm 02 44 33.0
END DESCRIPTION:
XS GIS Cut Line= 4
      1583870.67      6875351.31      1583592.48      6874924.16
      1583565.81      6874683.92      1583176.71      6874151.52
#Sta/Elev= 30
  4302.6 1684.50  4347.4 1683.95  4540.6 1683.76  4546.6 1684.08  4555.8 1683.52
  4592.0 1683.10  4604.9 1683.51  4613.1 1682.76  4664.5 1682.36  4685.5 1682.75
  4691.5 1683.44  4721.8 1682.02  4727.7 1679.72  4742.9 1680.89  4748.8 1679.94
  4758.0 1680.70  4764.0 1681.77  4834.2 1678.20  4889.0 1676.74  4997.6 1676.33
  4998.0 1675.83  5002.1 1675.83  5002.4 1676.33  5195.5 1676.55  5408.6 1678.58
  5509.0 1680.83  5573.9 1683.24  5631.2 1686.43  5659.6 1687.54  5713.5 1688.72
#Mann=4,-1,0
  4302.6    0.07       0  4347.4   0.035       0  4997.6   0.035       0
  5002.4   0.035       0
Bank Sta=4997.6,5002.4
Exp/Cntr=0.3,0.1

Type RM Length L Ch R = 1,22331,473,473,473
BEGIN DESCRIPTION:
Elm 02 44 32.0
END DESCRIPTION:
XS GIS Cut Line= 4
      1583945.74      6875269.21      1583925.07      6874748.03
      1583805.50      6874620.76      1583504.53      6873127.70
#Sta/Elev= 30
  4386.2 1683.28  4457.5 1681.94  4531.8 1681.95  4577.6 1680.19  4627.6 1680.41
  4674.8 1678.93  4737.7 1678.74  4807.7 1677.03  4857.8 1677.67  4897.8 1676.17
  4911.2 1676.55  4914.9 1677.93  4921.8 1678.20  4943.3 1675.42  4992.6 1675.68
  4997.6 1675.11  4998.0 1674.61  5002.5 1675.11  5115.8 1675.88  5350.5 1675.13
  5415.3 1675.90  5562.7 1675.52  5860.5 1676.70  6025.0 1678.54  6375.5 1679.41
  6472.1 1678.44  6513.4 1678.98  6564.4 1681.49  6596.2 1680.45  6605.5 1680.07
#Mann=5,-1,0
  4386.2    0.07       0  4674.8   0.035       0  4997.6   0.035       0
  5002.5   0.035       0  6596.2   0.063       0
Bank Sta=4997.6,5002.5
Exp/Cntr=0.3,0.1

Type RM Length L Ch R = 1,21858,418,418,418
BEGIN DESCRIPTION:
Elm 02 44 31.0
END DESCRIPTION:
XS GIS Cut Line= 3
      1584555.00      6875488.00      1584233.63      6874409.25
      1583932.08      6873271.43
#Sta/Elev= 30
  3874.4 1689.08  3891.0 1684.04  4184.2 1679.99  4257.5 1678.74  4390.2 1678.16
  4660.2 1675.77  4699.1 1675.46  4802.1 1675.06  4928.3 1674.33  4949.1 1676.03
  4997.4 1672.87  4997.8 1672.37  5002.7 1672.87  5003.2 1674.29  5015.5 1672.87
  5042.7 1673.24  5073.7 1679.66  5095.9 1682.87  5270.3 1682.41  5311.7 1680.44
  5346.9 1680.56  5394.4 1679.70  5456.5 1681.30  5597.9 1680.04  5653.0 1681.70
  5686.4 1680.75  5984.1 1681.60  6110.3 1683.85  6145.3 1687.79  6177.1 1689.09
#Mann=11,-1,0
  3874.4   0.035       0  4184.2    0.07       0  4257.5   0.035       0
  4390.2    0.07       0  4660.2   0.035       0  4699.1    0.07       0
  4802.1   0.035       0  4997.4   0.035       0  5002.7   0.035       0
  5346.9    0.07       0  5686.4   0.035       0
Bank Sta=4997.4,5002.7
Exp/Cntr=0.3,0.1

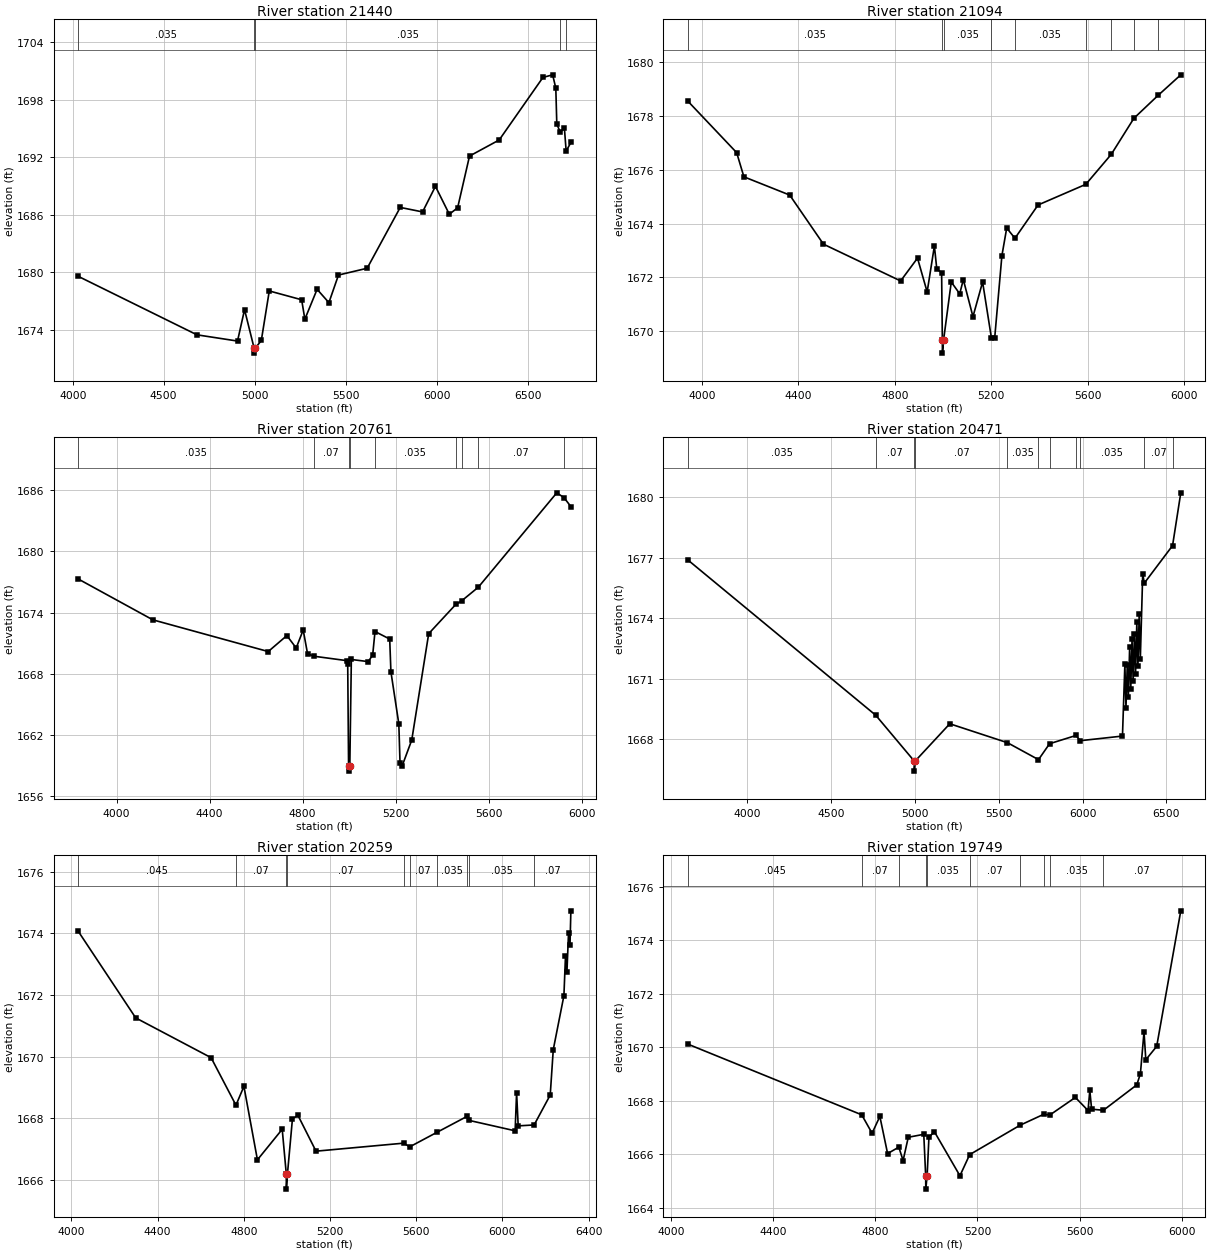
Type RM Length L Ch R = 1,21440,346,346,346
BEGIN DESCRIPTION:
Elm 02 44 30.8
END DESCRIPTION:
XS GIS Cut Line= 3
      1584826.82      6875062.12      1584450.40      6873837.85
      1583887.80      6872525.92
#Sta/Elev= 30
  4030.0 1679.56  4683.0 1673.45  4905.9 1672.80  4944.5 1676.08  4997.4 1672.04
  4997.8 1671.54  5002.7 1672.04  5036.7 1672.86  5080.5 1678.03  5258.4 1677.11
  5276.1 1675.08  5343.3 1678.20  5408.2 1676.81  5460.8 1679.69  5618.5 1680.40
  5800.3 1686.75  5923.1 1686.28  5993.8 1688.95  6070.0 1686.04  6115.8 1686.71
  6181.1 1692.11  6344.3 1693.79  6584.8 1700.32  6638.1 1700.59  6655.5 1699.20
  6661.0 1695.44  6680.3 1694.60  6702.7 1695.02  6712.4 1692.63  6738.3 1693.53
#Mann=5,-1,0
  4030.0   0.035       0  4997.4   0.035       0  5002.7   0.035       0
  6680.3   0.063       0  6712.4   0.035       0
Bank Sta=4997.4,5002.7
Exp/Cntr=0.3,0.1

Type RM Length L Ch R = 1,21094,333,333,333
BEGIN DESCRIPTION:
Elm 02 44 30.6
END DESCRIPTION:
XS GIS Cut Line= 3
      1584829.60      6874989.43      1584799.37      6873251.58
      1584730.80      6872953.89
#Sta/Elev= 30
  3942.8 1678.55  4144.3 1676.64  4174.3 1675.74  4364.3 1675.06  4504.3 1673.23
  4824.4 1671.86  4894.4 1672.71  4934.4 1671.45  4964.4 1673.16  4974.4 1672.30
  4994.4 1672.17  4997.4 1669.67  4997.8 1669.17  5002.7 1669.67  5034.4 1671.82
  5069.5 1671.38  5084.4 1671.91  5124.4 1670.53  5164.4 1671.82  5200.7 1669.75
  5214.4 1669.72  5244.4 1672.80  5264.4 1673.83  5298.6 1673.45  5394.4 1674.69
  5592.5 1675.46  5698.3 1676.58  5791.9 1677.92  5893.0 1678.78  5986.4 1679.54
#Mann=9,-1,0
  3942.8   0.035       0  4997.4   0.035       0  5002.7   0.035       0
  5200.7   0.063       0  5298.6   0.035       0  5592.5   0.063       0
  5698.3   0.125       0  5791.9   0.063       0  5893.0   0.094       0
Bank Sta=4997.4,5002.7
Exp/Cntr=0.3,0.1

Type RM Length L Ch R = 1,20761,290,290,290
BEGIN DESCRIPTION:
Elm 02 44 30.4
END DESCRIPTION:
XS GIS Cut Line= 3
      1584848.82      6874843.19      1584914.14      6873855.50
      1585220.36      6872769.70
#Sta/Elev= 30
  3835.0 1677.30  4155.9 1673.28  4652.0 1670.16  4732.1 1671.73  4772.2 1670.51
  4802.3 1672.28  4821.1 1669.94  4848.5 1669.70  4988.5 1669.27  4993.7 1668.89
  4997.4 1658.90  4997.8 1658.40  5002.7 1658.90  5009.3 1669.38  5082.0 1669.17
  5101.0 1669.82  5111.0 1672.13  5174.2 1671.39  5179.4 1668.17  5213.4 1663.05
  5218.6 1659.17  5227.5 1658.90  5269.0 1661.46  5341.8 1671.92  5458.1 1674.79
  5483.2 1675.14  5555.2 1676.49  5892.4 1685.77  5923.3 1685.30  5953.0 1684.42
#Mann=9,-1,0
  3835.0   0.035       0  4848.5    0.07       0  4997.4    0.07       0
  5002.7    0.07       0  5111.0   0.035       0  5458.1    0.07       0
  5483.2   0.035       0  5555.2    0.07       0  5923.3   0.035       0
Bank Sta=4997.4,5002.7
Exp/Cntr=0.3,0.1

Type RM Length L Ch R = 1,20471,212,212,212
BEGIN DESCRIPTION:
Elm 02 44 30.2
END DESCRIPTION:
XS GIS Cut Line= 4
      1584882.49      6874899.08      1584926.06      6873933.27
      1585961.05      6873068.31      1586368.78      6872601.66
#Sta/Elev= 30
  3649.9 1676.89  4768.3 1669.19  4997.2 1666.92  4997.7 1666.42  5002.8 1666.92
  5209.0 1668.77  5552.8 1667.83  5737.5 1666.99  5803.5 1667.78  5961.1 1668.19
  5986.1 1667.93  6237.8 1668.16  6252.1 1671.72  6258.7 1669.57  6266.3 1671.68
  6272.9 1670.10  6280.5 1672.56  6287.2 1670.52  6294.8 1672.96  6301.4 1670.88
  6309.0 1673.23  6315.7 1671.22  6323.3 1673.80  6329.9 1671.62  6337.5 1674.20
  6344.1 1671.97  6358.4 1676.20  6368.0 1675.75  6536.2 1677.61  6585.2 1680.23
#Mann=11,-1,0
  3649.9   0.035       0  4768.3    0.07       0  4997.2    0.07       0
  5002.8    0.07       0  5552.8   0.035       0  5737.5    0.07       0
  5803.5   0.035       0  5961.1    0.07       0  5986.1   0.035       0
  6368.0    0.07       0  6536.2   0.035       0
Bank Sta=4997.2,5002.8
Exp/Cntr=0.3,0.1

Type RM Length L Ch R = 1,20259,510,510,510
BEGIN DESCRIPTION:
Elm 02 44 30.0
END DESCRIPTION:
XS GIS Cut Line= 4
      1585151.07      6874613.78      1585475.25      6873545.86
      1585959.60      6873097.18      1586305.05      6872722.63
#Sta/Elev= 30
  4031.8 1674.07  4298.7 1671.26  4648.5 1669.97  4763.8 1668.43  4800.7 1669.04
  4863.4 1666.66  4978.4 1667.65  4997.2 1666.21  4997.7 1665.71  5002.8 1666.21
  5025.9 1667.99  5051.5 1668.10  5135.2 1666.94  5542.1 1667.20  5569.8 1667.08
  5696.0 1667.55  5836.5 1668.07  5844.0 1667.94  6059.0 1667.60  6065.8 1668.84
  6073.2 1667.76  6147.1 1667.79  6221.8 1668.76  6235.9 1670.23  6285.3 1671.98
  6292.6 1673.26  6299.4 1672.76  6306.8 1674.02  6313.6 1673.63  6317.6 1674.73
#Mann=10,-1,0
  4031.8   0.045       0  4763.8    0.07       0  4997.2    0.07       0
  5002.8    0.07       0  5542.1   0.035       0  5569.8    0.07       0
  5696.0   0.035       0  5836.5    0.07       0  5844.0   0.035       0
  6147.1    0.07       0
Bank Sta=4997.2,5002.8
Exp/Cntr=0.3,0.1

Type RM Length L Ch R = 1,19749,551,551,551
BEGIN DESCRIPTION:
Elm 02 44 29.0
END DESCRIPTION:
XS GIS Cut Line= 3
      1585757.46      6874460.13      1585958.04      6873124.61
      1586367.65      6872717.23
#Sta/Elev= 30
  4067.4 1670.11  4746.9 1667.47  4787.5 1666.78  4817.9 1667.41  4848.2 1666.02
  4892.1 1666.26  4908.9 1665.76  4929.1 1666.63  4989.8 1666.74  4997.2 1665.19
  4997.7 1664.69  5002.9 1665.19  5010.0 1666.63  5031.2 1666.84  5131.3 1665.19
  5169.4 1665.98  5366.6 1667.08  5459.3 1667.49  5482.8 1667.46  5583.0 1668.12
  5632.6 1667.63  5639.6 1668.38  5646.7 1667.68  5692.9 1667.64  5823.5 1668.59
  5837.6 1669.01  5851.7 1670.57  5858.8 1669.53  5901.3 1670.03  5995.6 1675.10
#Mann=10,-1,0
  4067.4   0.045       0  4746.9    0.07       0  4892.1   0.035       0
  4997.2   0.035       0  5002.9   0.035       0  5169.4    0.07       0
  5366.6   0.035       0  5459.3    0.07       0  5482.8   0.035       0
  5692.9    0.07       0
Bank Sta=4997.2,5002.9
Exp/Cntr=0.3,0.1

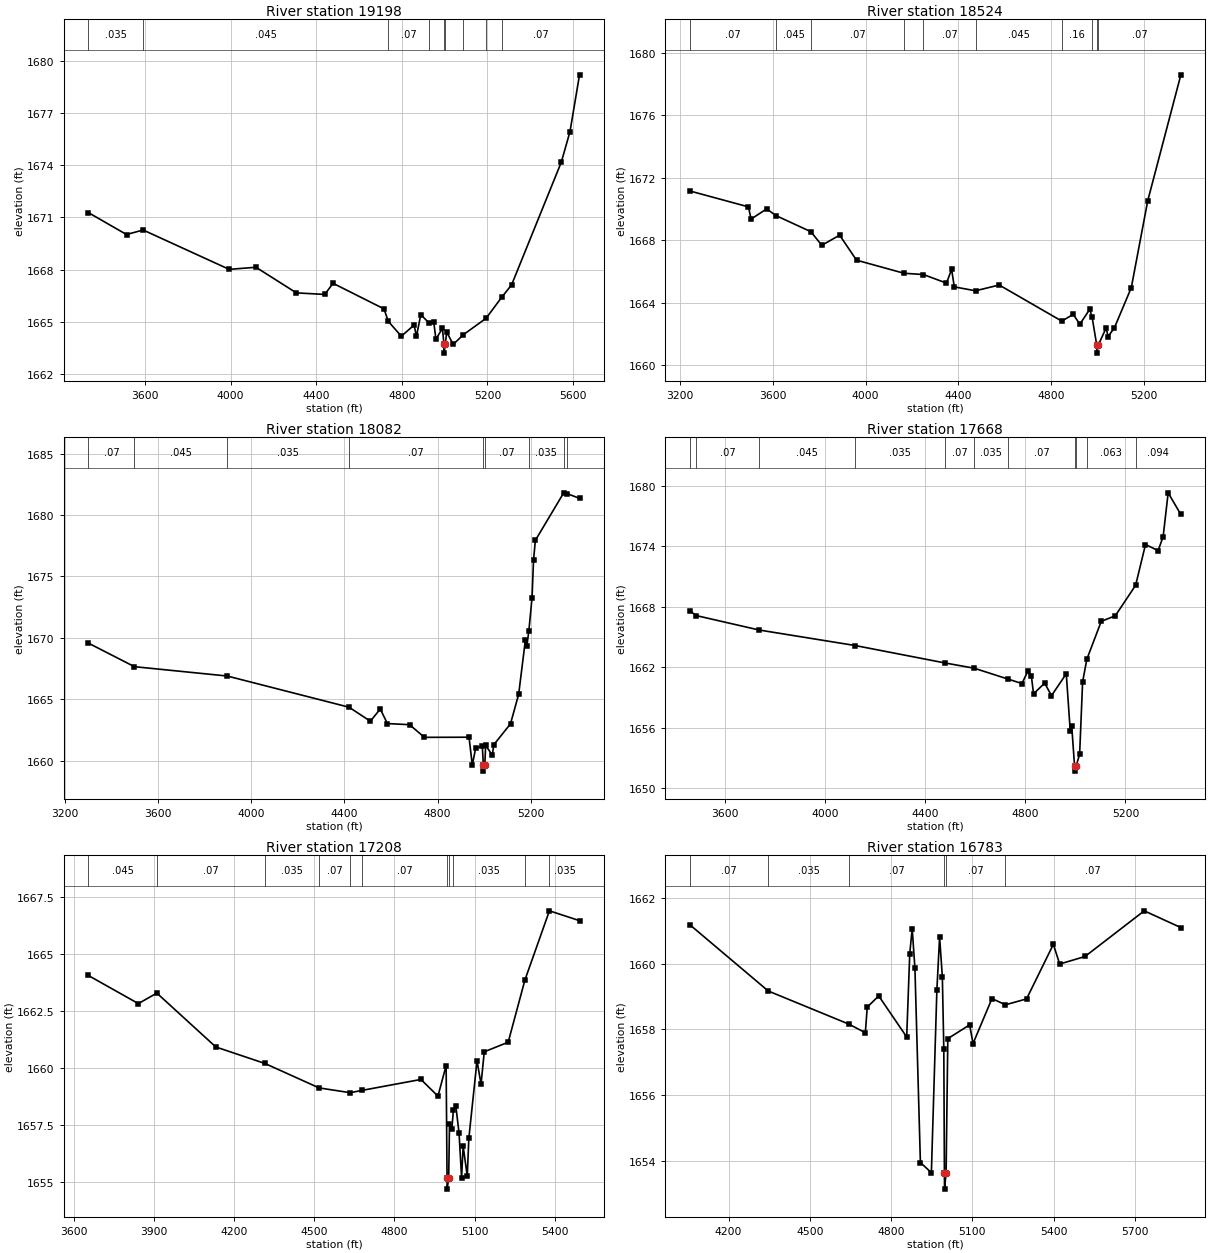
Type RM Length L Ch R = 1,19198,674,674,674
BEGIN DESCRIPTION:
Elm 02 44 28.2
END DESCRIPTION:
XS GIS Cut Line= 3
      1585894.73      6874899.00      1586229.80      6873769.60
      1586390.95      6872663.94
#Sta/Elev= 30
  3335.1 1671.28  3513.5 1670.02  3590.9 1670.28  3993.3 1668.02  4118.5 1668.14
  4307.2 1666.67  4440.1 1666.58  4478.5 1667.22  4716.9 1665.75  4736.5 1665.04
  4797.7 1664.18  4857.3 1664.82  4868.5 1664.18  4888.7 1665.42  4926.6 1664.95
  4949.3 1665.00  4959.4 1664.01  4989.7 1664.63  4997.1 1663.71  4997.6 1663.21
  5003.0 1663.71  5009.9 1664.42  5040.3 1663.71  5087.9 1664.27  5193.8 1665.21
  5267.1 1666.42  5313.1 1667.13  5545.5 1674.18  5586.0 1675.93  5630.5 1679.19
#Mann=9,-1,0
  3335.1   0.035       0  3590.9   0.045       0  4736.5    0.07       0
  4926.6   0.035       0  4997.1   0.035       0  5003.0   0.035       0
  5087.9    0.07       0  5193.8   0.035       0  5267.1    0.07       0
Bank Sta=4997.1,5003
Exp/Cntr=0.3,0.1

Type RM Length L Ch R = 1,18524,442,442,442
BEGIN DESCRIPTION:
Elm 02 44 28.0
END DESCRIPTION:
XS GIS Cut Line= 3
      1585941.36      6874963.31      1586595.59      6873689.53
      1587004.97      6873138.04
#Sta/Elev= 30
  3241.0 1671.15  3494.3 1670.13  3505.9 1669.35  3573.0 1670.00  3613.5 1669.57
  3763.9 1668.54  3810.9 1667.67  3887.8 1668.32  3960.6 1666.72  4165.7 1665.88
  4249.3 1665.80  4348.7 1665.25  4370.9 1666.13  4382.4 1665.01  4474.1 1664.76
  4576.2 1665.13  4846.0 1662.82  4895.6 1663.25  4924.0 1662.62  4966.6 1663.57
  4976.7 1663.10  4997.0 1661.27  4997.5 1660.77  5003.0 1661.27  5037.5 1662.38
  5045.9 1661.83  5073.4 1662.40  5146.0 1664.96  5216.9 1670.52  5359.8 1678.58
#Mann=10,-1,0
  3241.0    0.07       0  3613.5   0.045       0  3763.9    0.07       0
  4165.7   0.035       0  4249.3    0.07       0  4474.1   0.045       0
  4846.0    0.16       0  4976.7    0.07       0  4997.0    0.07       0
  5003.0    0.07       0
Bank Sta=4997,5003
Exp/Cntr=0.3,0.1

Type RM Length L Ch R = 1,18082,414,414,414
BEGIN DESCRIPTION:
Elm 02 44 27.0
END DESCRIPTION:
XS GIS Cut Line= 3
      1586447.83      6875152.13      1586873.55      6873935.14
      1587397.18      6873302.15
#Sta/Elev= 30
  3299.4 1669.57  3497.6 1667.65  3896.3 1666.89  4420.1 1664.35  4511.5 1663.21
  4553.9 1664.21  4584.5 1663.02  4679.8 1662.93  4743.6 1661.90  4935.4 1661.91
  4949.4 1659.65  4963.8 1661.00  4992.4 1661.18  4997.0 1659.65  4997.5 1659.15
  5003.1 1659.65  5006.8 1661.25  5035.4 1660.45  5041.9 1661.30  5113.6 1663.00
  5148.7 1665.41  5177.4 1669.79  5183.9 1669.33  5192.6 1670.59  5206.1 1673.25
  5212.6 1676.32  5220.4 1677.93  5342.3 1681.80  5357.5 1681.73  5410.2 1681.35
#Mann=9,-1,0
  3299.4    0.07       0  3497.6   0.045       0  3896.3   0.035       0
  4420.1    0.07       0  4997.0    0.07       0  5003.1    0.07       0
  5192.6   0.035       0  5342.3   0.094       0  5357.5   0.035       0
Bank Sta=4997,5003.1
Exp/Cntr=0.3,0.1

Type RM Length L Ch R = 1,17668,460,460,460
BEGIN DESCRIPTION:
Elm 02 44 26.0
END DESCRIPTION:
XS GIS Cut Line= 3
      1586713.66      6875149.01      1587531.16      6873721.79
      1587564.14      6873407.59
#Sta/Elev= 30
  3460.6 1667.59  3487.1 1667.12  3737.8 1665.69  4121.4 1664.15  4477.9 1662.43
  4596.3 1661.90  4731.5 1660.82  4787.1 1660.38  4810.1 1661.59  4824.4 1661.16
  4833.2 1659.36  4877.6 1660.42  4904.9 1659.18  4963.9 1661.35  4979.8 1655.65
  4985.5 1656.21  4997.0 1652.19  4997.5 1651.69  5003.1 1652.19  5017.2 1653.36
  5029.1 1660.54  5046.0 1662.79  5103.5 1666.55  5159.5 1667.10  5240.8 1670.13
  5280.1 1674.17  5330.4 1673.57  5350.5 1674.94  5370.6 1679.30  5421.3 1677.15
#Mann=11,-1,0
  3460.6   0.045       0  3487.1    0.07       0  3737.8   0.045       0
  4121.4   0.035       0  4477.9    0.07       0  4596.3   0.035       0
  4731.5    0.07       0  4997.0    0.07       0  5003.1    0.07       0
  5046.0   0.063       0  5240.8   0.094       0
Bank Sta=4997,5003.1
Exp/Cntr=0.3,0.1

Type RM Length L Ch R = 1,17208,425,425,425
BEGIN DESCRIPTION:
Elm 02 44 25.7
END DESCRIPTION:
XS GIS Cut Line= 4
      1587050.19      6874917.77      1587666.12      6874282.92
      1588008.11      6873737.83      1587903.84      6873446.88
#Sta/Elev= 30
  3655.3 1664.05  3842.4 1662.82  3911.5 1663.28  4132.3 1660.92  4315.6 1660.20
  4518.3 1659.13  4635.0 1658.92  4678.0 1659.02  4899.3 1659.50  4962.9 1658.77
  4993.5 1660.11  4996.9 1655.20  4997.4 1654.70  5003.1 1655.20  5006.1 1657.54
  5014.7 1657.31  5020.7 1658.16  5029.7 1658.35  5041.9 1657.14  5051.3 1655.20
  5057.2 1656.58  5072.5 1655.27  5078.4 1656.92  5109.0 1660.32  5124.1 1659.29
  5136.1 1660.71  5225.6 1661.13  5288.4 1663.86  5379.8 1666.88  5492.4 1666.45
#Mann=11,-1,0
  3655.3   0.045       0  3911.5    0.07       0  4315.6   0.035       0
  4518.3    0.07       0  4635.0   0.035       0  4678.0    0.07       0
  4996.9    0.07       0  5003.1    0.07       0  5020.7   0.035       0
  5288.4   0.063       0  5379.8   0.035       0
Bank Sta=4996.9,5003.1
Exp/Cntr=0.3,0.1

Type RM Length L Ch R = 1,16783,290,290,290
BEGIN DESCRIPTION:
Elm 02 44 25.6
END DESCRIPTION:
XS GIS Cut Line= 4
      1587372.90      6874792.78      1587884.81      6874286.66
      1588181.20      6874240.43      1588500.29      6873514.29
#Sta/Elev= 30
  4056.7 1661.19  4346.7 1659.17  4644.7 1658.16  4705.1 1657.90  4712.1 1658.68
  4754.5 1659.02  4857.7 1657.77  4869.0 1660.31  4878.0 1661.07  4888.1 1659.86
  4908.3 1653.95  4948.8 1653.64  4969.1 1659.20  4979.2 1660.81  4989.3 1659.60
  4994.7 1657.41  4996.9 1653.64  4997.4 1653.14  5003.1 1653.64  5009.5 1657.72
  5090.1 1658.14  5102.5 1657.57  5172.5 1658.94  5222.3 1658.75  5300.2 1658.93
  5399.1 1660.59  5422.4 1659.99  5515.8 1660.22  5734.6 1661.61  5869.7 1661.10
#Mann=6,-1,0
  4056.7    0.07       0  4346.7   0.035       0  4644.7    0.07       0
  4996.9   0.035       0  5003.1    0.07       0  5222.3    0.07       0
Bank Sta=4996.9,5003.1
Exp/Cntr=0.3,0.1

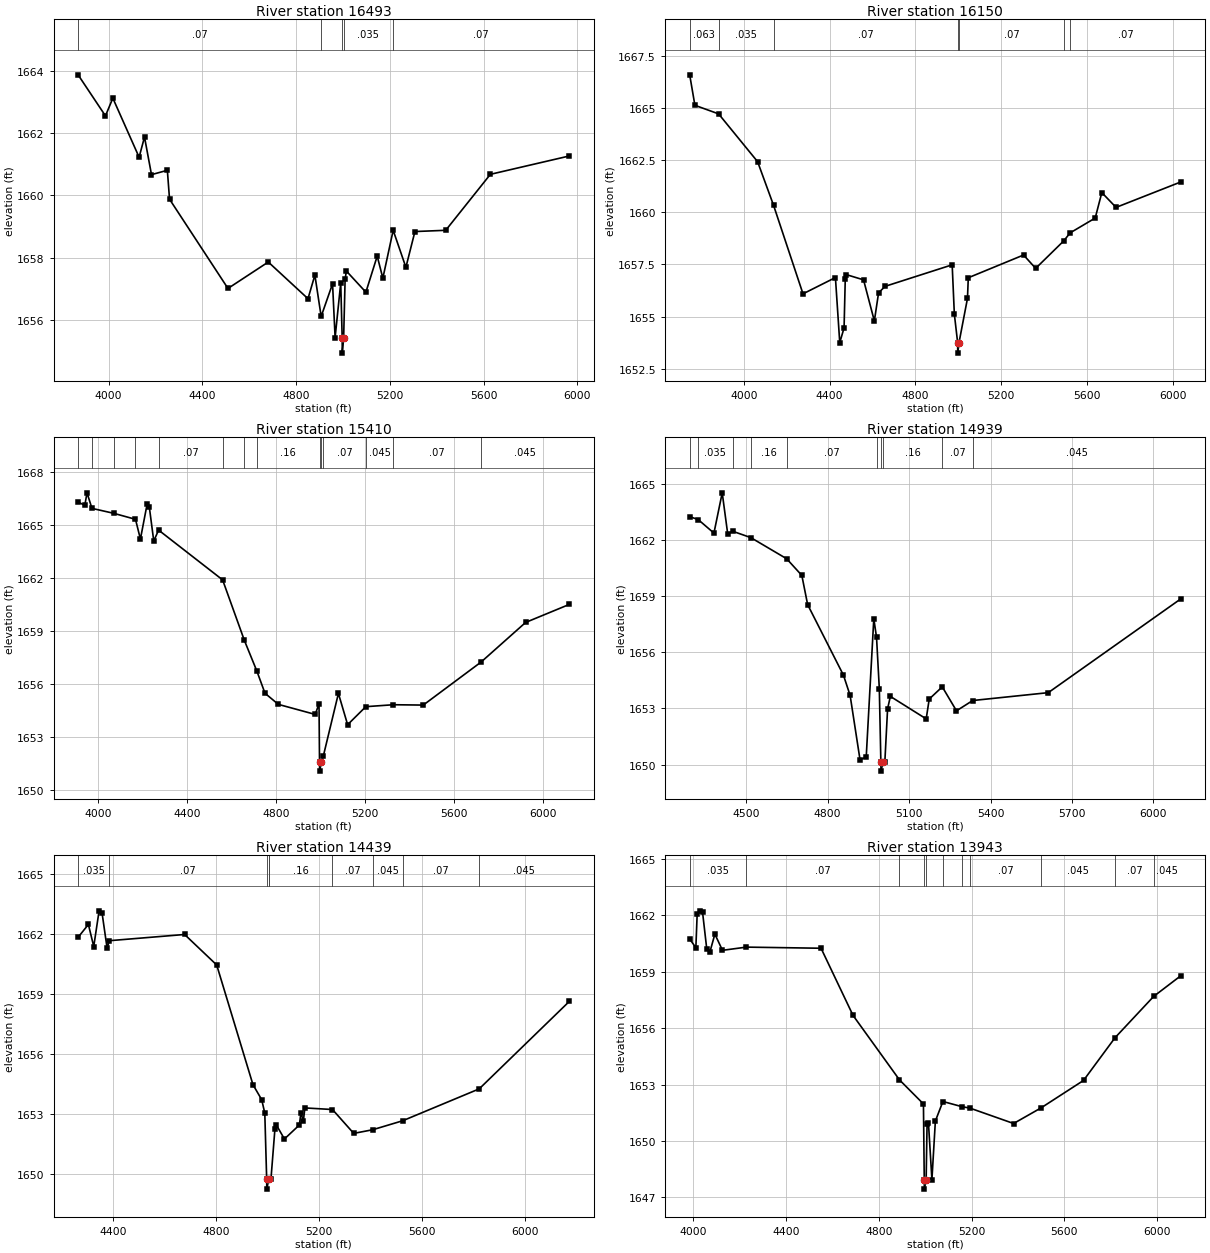
Type RM Length L Ch R = 1,16493,343,343,343
BEGIN DESCRIPTION:
Elm 02 44 25.5
END DESCRIPTION:
XS GIS Cut Line= 4
      1587693.04      6875532.70      1588053.16      6874746.28
      1588163.34      6874569.75      1588546.46      6873621.79
#Sta/Elev= 30
  3870.3 1663.88  3987.0 1662.56  4018.5 1663.13  4130.6 1661.23  4153.6 1661.88
  4183.4 1660.67  4251.1 1660.81  4260.4 1659.88  4509.7 1657.01  4681.7 1657.86
  4851.1 1656.68  4880.5 1657.44  4907.3 1656.11  4955.9 1657.16  4966.8 1655.43
  4990.8 1657.19  4996.9 1655.43  4997.4 1654.93  5003.2 1655.43  5009.5 1657.31
  5014.9 1657.57  5098.1 1656.89  5146.4 1658.05  5170.5 1657.34  5214.5 1658.88
  5268.8 1657.69  5307.3 1658.84  5438.7 1658.88  5629.2 1660.68  5965.8 1661.27
#Mann=5,-1,0
  3870.3    0.07       0  4907.3   0.035       0  4996.9   0.035       0
  5003.2   0.035       0  5214.5    0.07       0
Bank Sta=4996.9,5003.2
Exp/Cntr=0.3,0.1

Type RM Length L Ch R = 1,16150,740,740,740
BEGIN DESCRIPTION:
Elm 02 44 25.3
END DESCRIPTION:
XS GIS Cut Line= 4
      1588481.07      6876032.06      1588329.39      6874832.79
      1588339.24      6874747.19      1588570.25      6873779.57
#Sta/Elev= 30
  3747.7 1666.58  3772.0 1665.12  3882.4 1664.71  4064.3 1662.42  4138.7 1660.33
  4275.9 1656.09  4427.1 1656.87  4447.3 1653.75  4467.4 1654.46  4473.0 1656.81
  4478.0 1657.01  4558.2 1656.76  4608.6 1654.79  4628.3 1656.14  4659.0 1656.45
  4971.4 1657.48  4981.5 1655.12  4996.9 1653.75  4997.4 1653.25  5003.2 1653.75
  5042.7 1655.87  5046.5 1656.86  5304.2 1657.95  5360.6 1657.31  5491.9 1658.63
  5521.3 1659.01  5638.2 1659.72  5669.0 1660.94  5735.4 1660.23  6037.5 1661.45
#Mann=7,-1,0
  3747.7   0.063       0  3882.4   0.035       0  4138.7    0.07       0
  4996.9    0.07       0  5003.2    0.07       0  5491.9   0.045       0
  5521.3    0.07       0
Bank Sta=4996.9,5003.2
Exp/Cntr=0.3,0.1

Type RM Length L Ch R = 1,15410,471,471,471
BEGIN DESCRIPTION:
Elm 02 44 25.2
END DESCRIPTION:
XS GIS Cut Line= 4
      1588735.54      6876348.10      1588733.92      6875428.26
      1588813.25      6875156.80      1588792.30      6874151.87
#Sta/Elev= 30
  3910.8 1666.31  3940.9 1666.12  3950.9 1666.83  3973.0 1665.95  4070.9 1665.67
  4168.8 1665.33  4190.9 1664.21  4220.9 1666.18  4230.9 1666.03  4250.9 1664.10
  4272.6 1664.72  4560.4 1661.90  4658.3 1658.47  4714.2 1656.74  4750.9 1655.48
  4810.9 1654.85  4976.8 1654.28  4993.7 1654.89  4996.0 1651.57  4996.5 1651.07
  5004.0 1651.57  5013.4 1651.94  5080.9 1655.47  5122.3 1653.70  5204.1 1654.72
  5328.2 1654.83  5462.3 1654.81  5722.5 1657.25  5922.4 1659.49  6118.6 1660.51
#Mann=14,-1,0
  3910.8   0.045       0  3973.0    0.07       0  4070.9   0.045       0
  4168.8   0.035       0  4272.6    0.07       0  4560.4    0.16       0
  4658.3    0.07       0  4714.2    0.16       0  4996.0    0.07       0
  5004.0    0.16       0  5013.4    0.07       0  5204.1   0.045       0
  5328.2    0.07       0  5722.5   0.045       0
Bank Sta=4996,5004
Exp/Cntr=0.3,0.1

Type RM Length L Ch R = 1,14939,500,500,500
BEGIN DESCRIPTION:
Elm 02 44 25.1
END DESCRIPTION:
XS GIS Cut Line= 3
      1589292.29      6876135.97      1589115.50      6875131.61
      1588850.08      6874388.06
#Sta/Elev= 30
  4291.8 1663.24  4323.2 1663.08  4381.1 1662.36  4411.6 1664.51  4431.9 1662.31
  4449.7 1662.46  4516.8 1662.12  4649.0 1660.99  4704.9 1660.10  4726.3 1658.54
  4858.3 1654.77  4882.8 1653.69  4919.3 1650.25  4942.1 1650.41  4970.0 1657.79
  4980.1 1656.79  4990.3 1654.06  4996.0 1650.15  4996.5 1649.65  5004.1 1650.15
  5010.7 1650.15  5020.8 1652.98  5031.0 1653.64  5163.0 1652.44  5174.2 1653.50
  5222.2 1654.15  5274.6 1652.87  5334.3 1653.42  5612.7 1653.84  6101.1 1658.85
#Mann=10,-1,0
  4291.8   0.045       0  4323.2   0.035       0  4449.7    0.07       0
  4516.8    0.16       0  4649.0    0.07       0  4980.1    0.16       0
  4996.0    0.07       0  5004.1    0.16       0  5222.2    0.07       0
  5334.3   0.045       0
Bank Sta=4996,5004.1
Exp/Cntr=0.3,0.1

Type RM Length L Ch R = 1,14439,496,496,496
BEGIN DESCRIPTION:
Elm 02 44 25.0
END DESCRIPTION:
XS GIS Cut Line= 3
      1589814.28      6876086.54      1589614.67      6875377.09
      1589005.80      6874375.42
#Sta/Elev= 30
  4263.0 1661.82  4303.0 1662.46  4323.8 1661.36  4344.6 1663.14  4356.4 1663.01
  4375.8 1661.27  4384.1 1661.65  4677.0 1661.96  4801.7 1660.44  4942.7 1654.47
  4976.7 1653.72  4988.7 1653.05  4996.0 1649.76  4996.5 1649.26  5004.1 1649.76
  5005.9 1649.76  5012.7 1649.77  5028.2 1652.28  5034.1 1652.45  5065.0 1651.76
  5123.2 1652.46  5129.0 1653.07  5138.6 1652.66  5144.5 1653.31  5251.8 1653.23
  5334.4 1652.04  5407.6 1652.22  5524.7 1652.67  5822.1 1654.26  6172.2 1658.62
#Mann=9,-1,0
  4263.0   0.035       0  4384.1    0.07       0  4996.0    0.07       0
  5004.1    0.07       0  5005.9    0.16       0  5251.8    0.07       0
  5407.6   0.045       0  5524.7    0.07       0  5822.1   0.045       0
Bank Sta=4996,5004.1
Exp/Cntr=0.3,0.1

Type RM Length L Ch R = 1,13943,356,356,356
BEGIN DESCRIPTION:
Elm 02 44 24.0
END DESCRIPTION:
XS GIS Cut Line= 3
      1590290.42      6876037.66      1589887.05      6875106.04
      1589260.44      6874199.28
#Sta/Elev= 30
  3984.8 1660.74  4011.4 1660.28  4017.1 1662.09  4028.0 1662.24  4040.3 1662.16
  4058.3 1660.22  4071.6 1660.04  4093.4 1661.00  4126.1 1660.14  4229.5 1660.31
  4551.1 1660.25  4688.9 1656.68  4889.2 1653.25  4992.5 1651.97  4996.0 1647.94
  4996.5 1647.44  5004.1 1647.94  5008.1 1650.90  5014.1 1650.96  5029.0 1647.94
  5043.9 1651.06  5076.4 1652.10  5160.1 1651.82  5192.6 1651.75  5381.2 1650.93
  5499.5 1651.76  5682.6 1653.22  5818.3 1655.49  5985.1 1657.69  6102.2 1658.79
#Mann=11,-1,0
  3984.8   0.035       0  4229.5    0.07       0  4889.2    0.16       0
  4996.0    0.07       0  5004.1    0.16       0  5076.4    0.07       0
  5160.1   0.045       0  5192.6    0.07       0  5499.5   0.045       0
  5818.3    0.07       0  5985.1   0.045       0
Bank Sta=4996,5004.1
Exp/Cntr=0.3,0.1