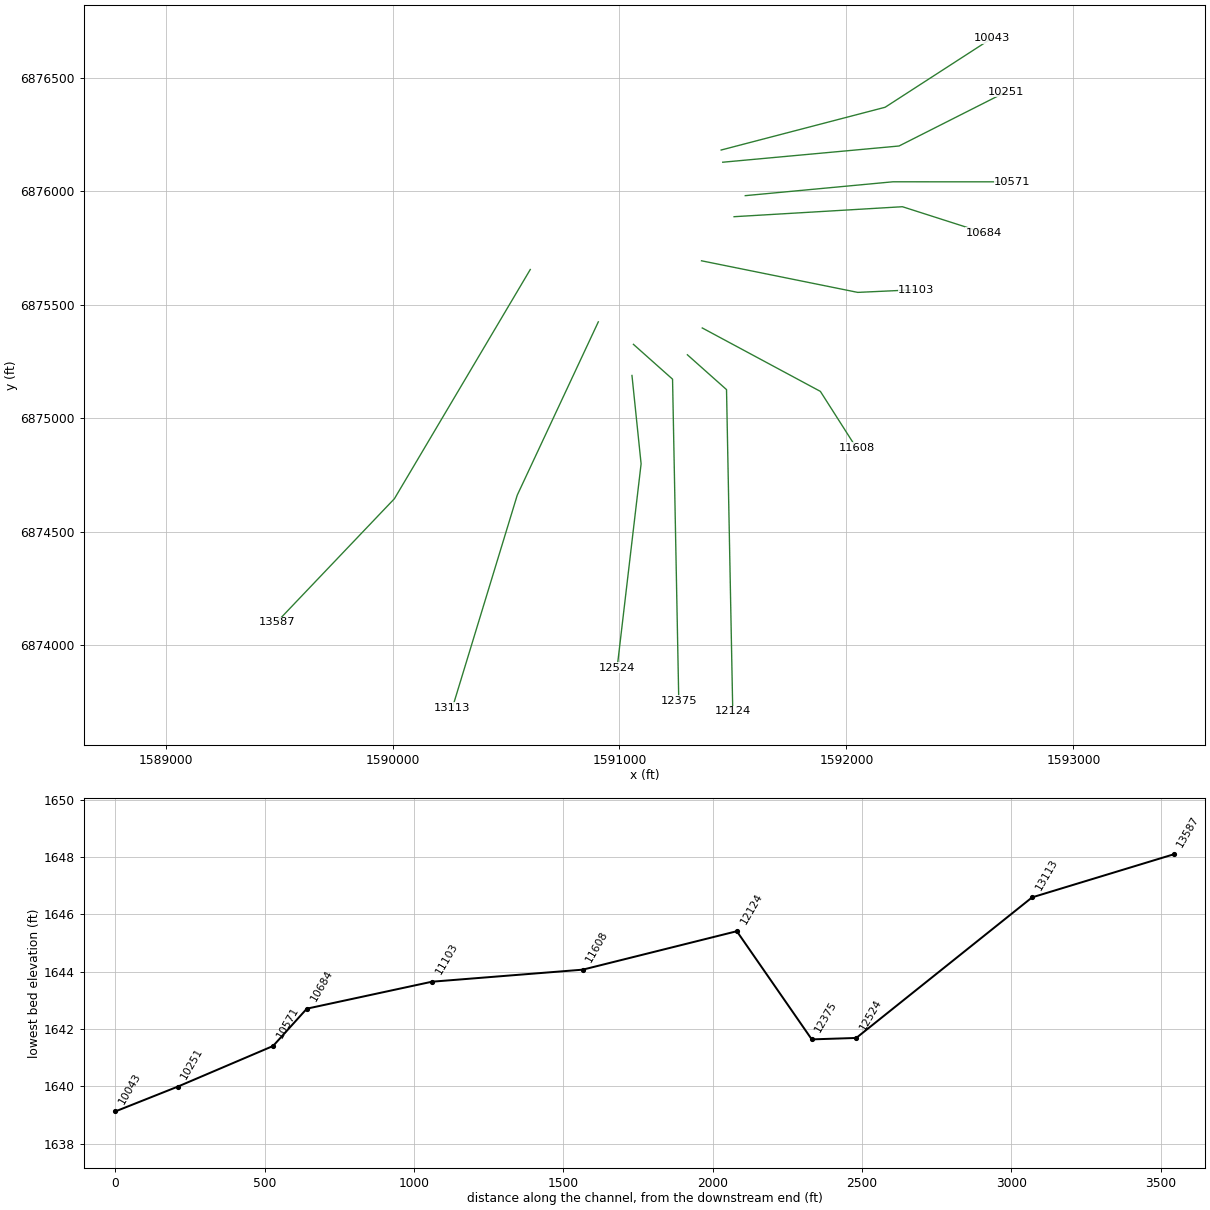
HEC-RAS study Elm 02 44.prj: Elm 02 44 Base Level Engineering

--- Elm 02 44.g01 (geometry) --- (continued)

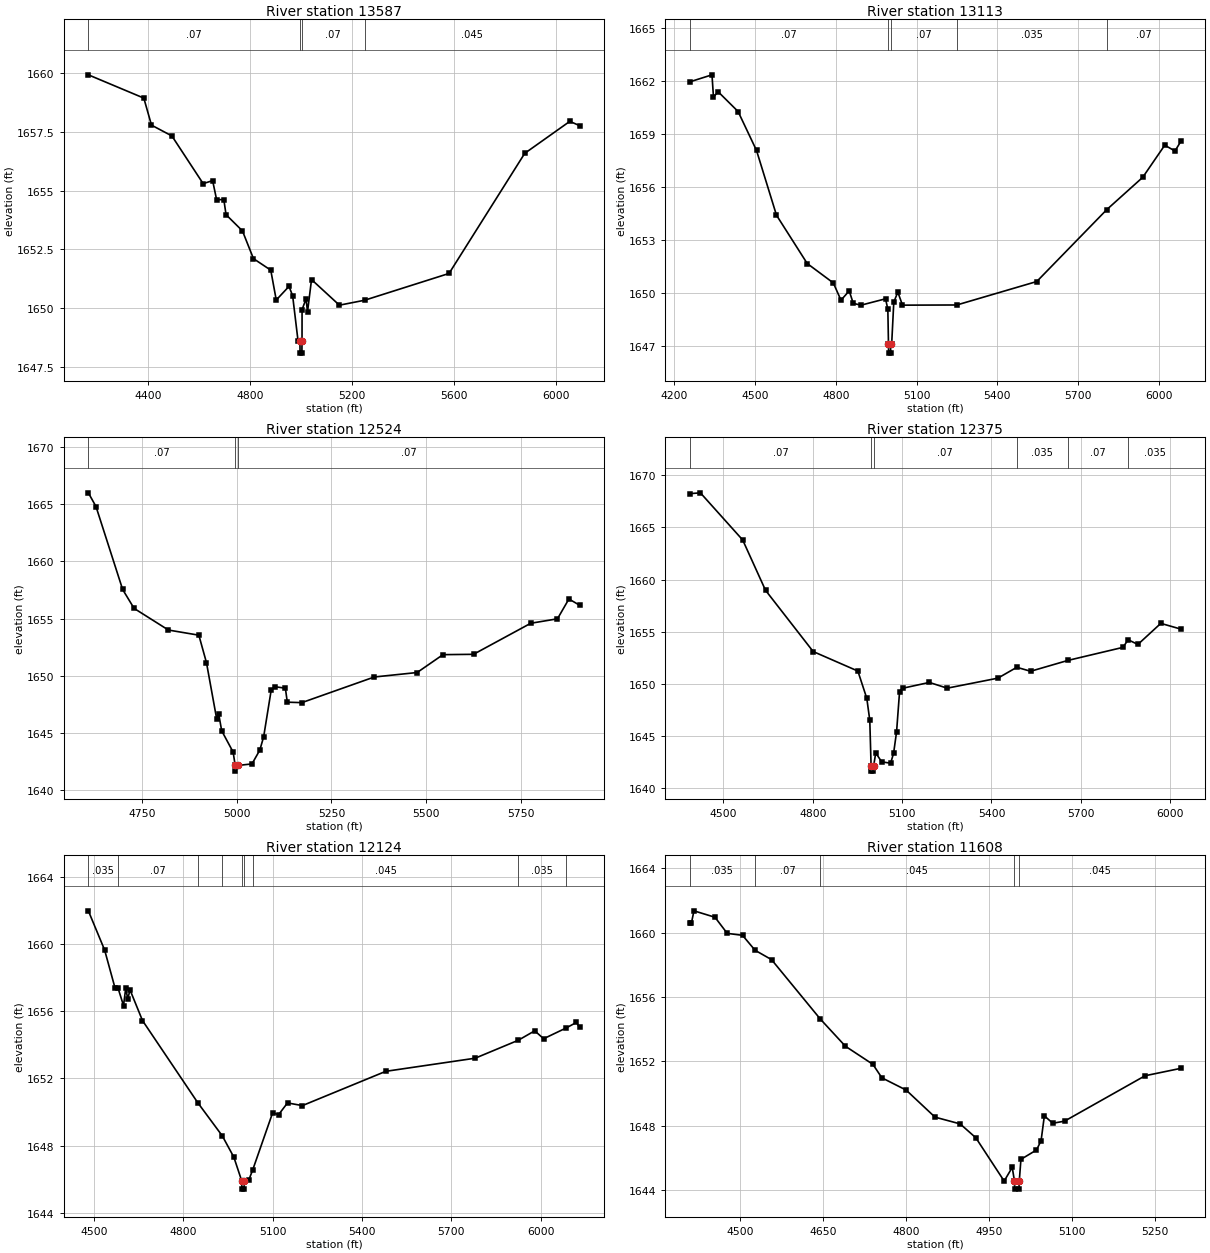
Type RM Length L Ch R = 1,13587,474,474,474
BEGIN DESCRIPTION:
Elm 02 44 23.0
END DESCRIPTION:
XS GIS Cut Line= 3
      1590606.83      6875655.22      1590008.28      6874645.02
      1589489.26      6874100.04
#Sta/Elev= 30
  4165.9 1659.93  4383.5 1658.94  4413.6 1657.79  4493.6 1657.33  4616.3 1655.30
  4653.4 1655.43  4669.0 1654.62  4697.4 1654.62  4706.1 1653.98  4770.4 1653.29
  4813.6 1652.11  4881.5 1651.62  4903.0 1650.35  4953.1 1650.93  4967.3 1650.53
  4988.7 1648.59  4995.9 1648.59  4996.4 1648.09  5003.6 1648.09  5004.1 1648.59
  5004.3 1649.94  5019.9 1650.40  5025.7 1649.85  5041.4 1651.22  5150.7 1650.13
  5249.5 1650.34  5580.9 1651.48  5877.8 1656.59  6054.6 1657.95  6092.7 1657.77
#Mann=4,-1,0
  4165.9    0.07       0  4995.9    0.07       0  5004.1    0.07       0
  5249.5   0.045       0
Bank Sta=4995.9,5004.1
Exp/Cntr=0.3,0.1

Type RM Length L Ch R = 1,13113,589,589,589
BEGIN DESCRIPTION:
Elm 02 44 22.0
END DESCRIPTION:
XS GIS Cut Line= 3
      1590906.71      6875424.53      1590549.39      6874660.34
      1590263.51      6873722.65
#Sta/Elev= 30
  4257.7 1661.97  4340.5 1662.37  4346.0 1661.11  4363.4 1661.41  4437.4 1660.29
  4505.9 1658.08  4580.0 1654.41  4694.2 1651.67  4791.1 1650.57  4819.5 1649.59
  4850.0 1650.12  4865.2 1649.41  4894.1 1649.31  4984.9 1649.67  4993.5 1649.08
  4995.9 1647.09  4996.4 1646.59  5003.6 1646.59  5004.1 1647.09  5007.7 1647.09
  5015.6 1649.48  5030.6 1650.05  5047.9 1649.31  5249.7 1649.32  5546.5 1650.65
  5806.7 1654.73  5940.1 1656.56  6021.8 1658.38  6059.8 1658.05  6081.6 1658.60
#Mann=5,-1,0
  4257.7    0.07       0  4995.9    0.07       0  5004.1    0.07       0
  5249.7   0.035       0  5806.7    0.07       0
Bank Sta=4995.9,5004.1
Exp/Cntr=0.3,0.1

Type RM Length L Ch R = 1,12524,149,149,149
BEGIN DESCRIPTION:
Elm 02 44 21.0
END DESCRIPTION:
XS GIS Cut Line= 3
      1591054.99      6875188.05      1591095.20      6874798.52
      1590989.67      6873900.20
#Sta/Elev= 30
  4608.4 1665.99  4628.6 1664.79  4698.9 1657.55  4729.1 1655.90  4819.6 1654.01
  4900.0 1653.56  4920.1 1651.16  4947.3 1646.20  4952.3 1646.69  4960.3 1645.21
  4990.5 1643.35  4995.8 1642.19  4996.3 1641.69  5004.3 1642.19  5040.2 1642.32
  5060.9 1643.53  5071.0 1644.69  5091.1 1648.81  5101.2 1649.06  5128.3 1648.93
  5133.4 1647.71  5171.7 1647.67  5363.0 1649.91  5476.0 1650.30  5544.2 1651.86
  5624.8 1651.89  5775.8 1654.60  5846.3 1654.99  5876.5 1656.72  5904.5 1656.18
#Mann=3,-1,0
  4608.4    0.07       0  4995.8    0.07       0  5004.3    0.07       0
Bank Sta=4995.8,5004.3
Exp/Cntr=0.3,0.1

Type RM Length L Ch R = 1,12375,251,251,251
BEGIN DESCRIPTION:
Elm 02 44 20.5
END DESCRIPTION:
XS GIS Cut Line= 3
      1591061.40      6875325.28      1591233.80      6875171.79
      1591261.26      6873753.68
#Sta/Elev= 30
  4386.7 1668.23  4422.6 1668.31  4564.7 1663.79  4641.3 1658.97  4801.3 1653.10
  4951.4 1651.23  4981.4 1648.61  4991.4 1646.51  4995.8 1642.14  4996.3 1641.64
  5003.8 1641.64  5004.3 1642.14  5011.4 1643.38  5031.4 1642.53  5061.4 1642.40
  5071.4 1643.36  5081.4 1645.42  5091.4 1649.26  5101.4 1649.58  5191.4 1650.14
  5251.4 1649.59  5421.5 1650.55  5485.0 1651.59  5531.5 1651.21  5656.7 1652.25
  5841.5 1653.50  5858.9 1654.23  5891.6 1653.78  5968.6 1655.80  6035.9 1655.25
#Mann=6,-1,0
  4386.7    0.07       0  4995.8    0.07       0  5004.3    0.07       0
  5485.0   0.035       0  5656.7    0.07       0  5858.9   0.035       0
Bank Sta=4995.8,5004.3
Exp/Cntr=0.3,0.1

Type RM Length L Ch R = 1,12124,516,516,516
BEGIN DESCRIPTION:
Elm 02 44 20.0
END DESCRIPTION:
XS GIS Cut Line= 3
      1591299.21      6875279.25      1591471.63      6875125.73
      1591499.11      6873707.66
#Sta/Elev= 30
  4480.9 1661.97  4535.5 1659.64  4570.6 1657.37  4580.3 1657.39  4599.0 1656.33
  4606.5 1657.38  4613.2 1656.71  4620.7 1657.27  4662.7 1655.44  4848.0 1650.56
  4930.6 1648.58  4969.5 1647.31  4995.7 1645.91  4996.2 1645.41  5003.8 1645.41
  5004.3 1645.91  5019.5 1645.95  5032.5 1646.54  5099.6 1649.95  5119.6 1649.84
  5149.6 1650.54  5199.6 1650.38  5479.6 1652.42  5779.7 1653.20  5924.6 1654.27
  5979.7 1654.83  6009.7 1654.36  6085.3 1655.00  6119.8 1655.33  6130.1 1655.03
#Mann=9,-1,0
  4480.9   0.035       0  4580.3    0.07       0  4848.0   0.045       0
  4930.6    0.07       0  4995.7    0.07       0  5004.3    0.07       0
  5032.5   0.045       0  5924.6   0.035       0  6085.3    0.07       0
Bank Sta=4995.7,5004.3
Exp/Cntr=0.3,0.1

Type RM Length L Ch R = 1,11608,505,505,505
BEGIN DESCRIPTION:
Elm 02 44 19.0
END DESCRIPTION:
XS GIS Cut Line= 3
      1591364.77      6875397.51      1591885.22      6875117.91
      1592044.46      6874868.16
#Sta/Elev= 30
  4409.2 1660.57  4412.2 1660.57  4416.9 1661.35  4454.9 1660.95  4477.0 1659.95
  4504.6 1659.83  4527.3 1658.90  4557.0 1658.32  4645.1 1654.63  4690.5 1652.94
  4740.0 1651.82  4756.3 1650.98  4800.1 1650.22  4852.2 1648.54  4897.6 1648.12
  4925.9 1647.26  4977.1 1644.57  4991.7 1645.42  4995.7 1644.57  4996.2 1644.07
  5003.9 1644.07  5004.4 1644.57  5007.4 1645.92  5035.5 1646.50  5043.8 1647.08
  5049.7 1648.62  5064.9 1648.16  5086.1 1648.29  5231.6 1651.11  5296.2 1651.57
#Mann=5,-1,0
  4409.2   0.035       0  4527.3    0.07       0  4645.1   0.045       0
  4995.7   0.045       0  5004.4   0.045       0
Bank Sta=4995.7,5004.4
Exp/Cntr=0.3,0.1

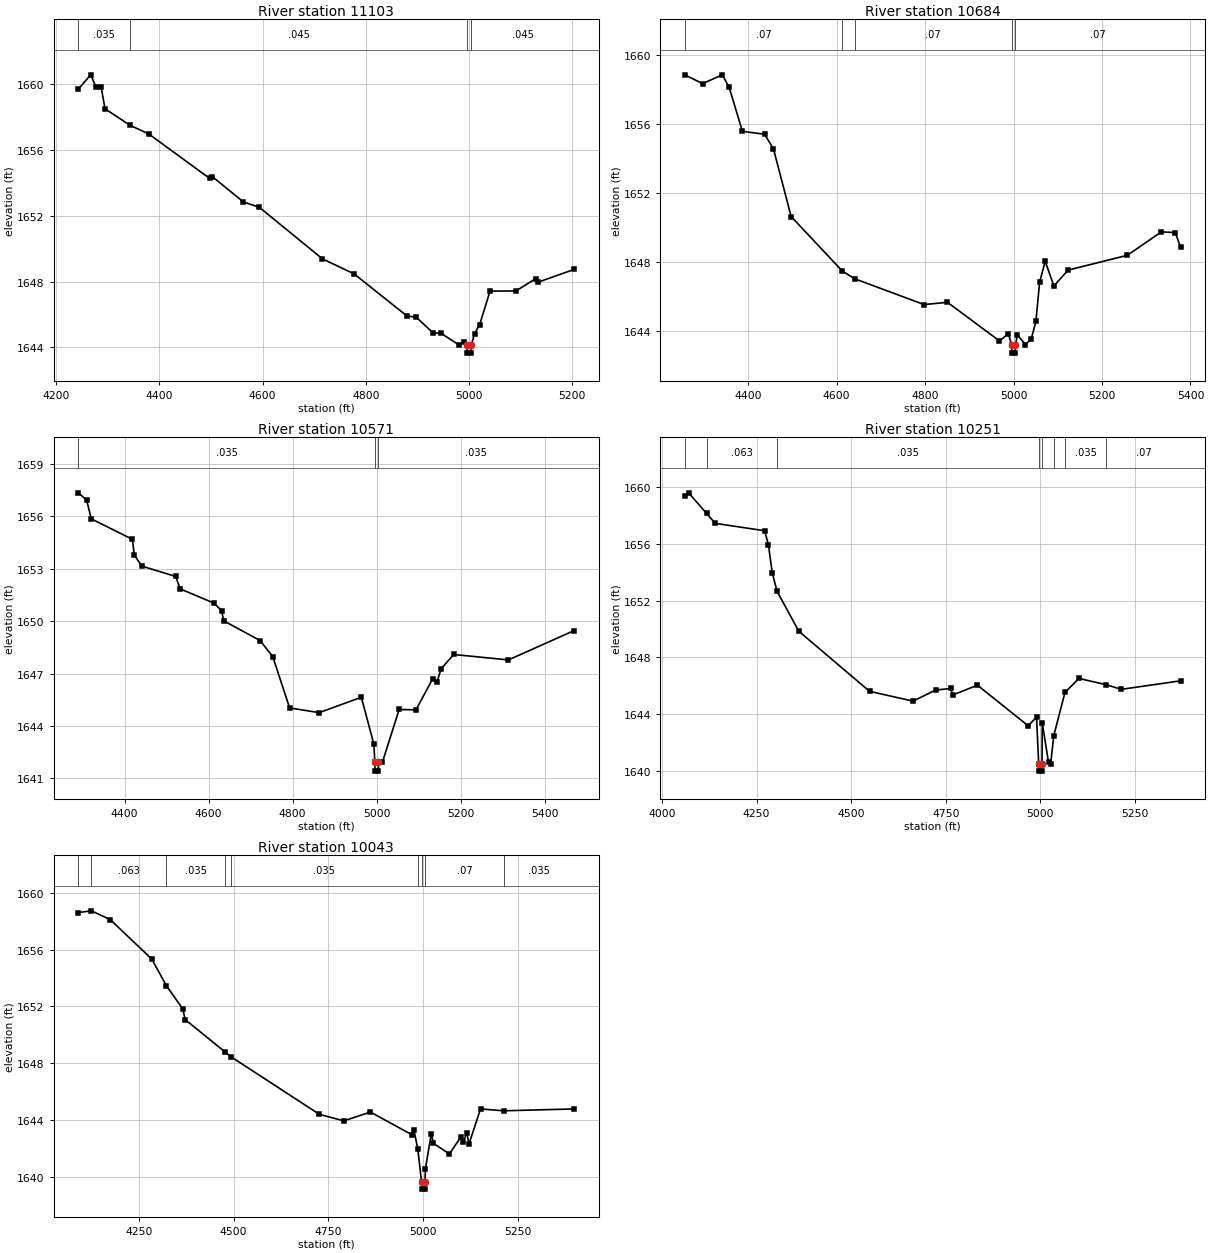
Type RM Length L Ch R = 1,11103,419,419,419
BEGIN DESCRIPTION:
Elm 02 44 18.0
END DESCRIPTION:
XS GIS Cut Line= 3
      1591361.44      6875693.63      1592049.89      6875554.34
      1592307.81      6875566.26
#Sta/Elev= 30
  4242.9 1659.70  4266.9 1660.57  4277.1 1659.83  4287.3 1659.80  4294.5 1658.51
  4343.0 1657.50  4379.2 1656.98  4497.4 1654.27  4502.5 1654.38  4562.8 1652.84
  4593.4 1652.52  4715.9 1649.38  4777.1 1648.47  4879.1 1645.92  4898.0 1645.82
  4930.1 1644.88  4945.3 1644.86  4980.4 1644.15  4990.5 1644.35  4995.7 1644.15
  4996.2 1643.65  5003.9 1643.65  5004.4 1644.15  5010.5 1644.83  5020.5 1645.39
  5040.5 1647.42  5090.6 1647.43  5129.2 1648.18  5134.2 1647.97  5203.5 1648.74
#Mann=4,-1,0
  4242.9   0.035       0  4343.0   0.045       0  4995.7   0.045       0
  5004.4   0.045       0
Bank Sta=4995.7,5004.4
Exp/Cntr=0.3,0.1

Type RM Length L Ch R = 1,10684,113,113,113
BEGIN DESCRIPTION:
Elm 02 44 17.0
END DESCRIPTION:
XS GIS Cut Line= 3
      1591505.01      6875888.00      1592246.81      6875931.97
      1592606.53      6875816.81
#Sta/Elev= 30
  4256.9 1658.87  4297.0 1658.36  4341.7 1658.87  4357.1 1658.15  4387.1 1655.59
  4437.2 1655.42  4457.2 1654.58  4497.3 1650.64  4613.2 1647.47  4640.7 1647.03
  4797.8 1645.53  4850.7 1645.66  4968.1 1643.42  4988.2 1643.83  4995.7 1643.21
  4996.2 1642.71  5003.9 1642.71  5004.4 1643.21  5008.6 1643.77  5026.9 1643.21
  5040.1 1643.54  5050.6 1644.55  5059.0 1646.84  5071.6 1648.04  5091.2 1646.61
  5123.3 1647.53  5257.2 1648.39  5334.1 1649.75  5365.6 1649.71  5377.7 1648.86
#Mann=5,-1,0
  4256.9    0.07       0  4613.2   0.045       0  4640.7    0.07       0
  4995.7    0.07       0  5004.4    0.07       0
Bank Sta=4995.7,5004.4
Exp/Cntr=0.3,0.1

Type RM Length L Ch R = 1,10571,320,320,320
BEGIN DESCRIPTION:
Elm 02 44 16.0
END DESCRIPTION:
XS GIS Cut Line= 3
      1591554.35      6875980.79      1592204.69      6876041.85
      1592731.49      6876041.68
#Sta/Elev= 30
  4290.1 1657.35  4309.8 1656.94  4320.9 1655.86  4418.5 1654.69  4423.5 1653.78
  4441.4 1653.15  4521.8 1652.56  4532.3 1651.85  4612.2 1651.04  4631.0 1650.61
  4636.0 1650.02  4722.6 1648.89  4752.8 1647.97  4792.9 1645.03  4863.3 1644.76
  4963.6 1645.64  4993.6 1642.94  4995.7 1641.91  4996.2 1641.41  5003.9 1641.41
  5004.4 1641.91  5013.6 1641.91  5053.6 1644.94  5093.6 1644.92  5133.6 1646.71
  5143.6 1646.51  5153.6 1647.28  5183.6 1648.09  5313.6 1647.78  5470.1 1649.46
#Mann=3,-1,0
  4290.1   0.035       0  4995.7   0.035       0  5004.4   0.035       0
Bank Sta=4995.7,5004.4
Exp/Cntr=0.3,0.1

Type RM Length L Ch R = 1,10251,208,208,208
BEGIN DESCRIPTION:
Elm 02 44 15.0
END DESCRIPTION:
XS GIS Cut Line= 3
      1591454.96      6876128.14      1592231.80      6876199.66
      1592704.74      6876438.83
#Sta/Elev= 30
  4060.5 1659.34  4070.6 1659.59  4118.1 1658.14  4140.9 1657.44  4271.4 1656.92
  4281.5 1655.93  4291.5 1653.96  4304.4 1652.65  4361.8 1649.84  4548.7 1645.61
  4663.5 1644.92  4723.3 1645.70  4763.2 1645.81  4768.2 1645.35  4833.8 1646.04
  4967.5 1643.19  4989.9 1643.78  4995.6 1640.49  4996.1 1639.99  5003.9 1639.99
  5004.4 1640.49  5004.9 1643.39  5021.6 1640.60  5027.2 1640.49  5035.3 1642.48
  5065.0 1645.53  5101.9 1646.52  5174.4 1646.07  5214.0 1645.75  5370.6 1646.35
#Mann=8,-1,0
  4060.5   0.035       0  4118.1   0.063       0  4304.4   0.035       0
  4995.6   0.035       0  5004.4   0.035       0  5035.3    0.07       0
  5065.0   0.035       0  5174.4    0.07       0
Bank Sta=4995.6,5004.4
Exp/Cntr=0.3,0.1

Type RM Length L Ch R = 1,10043,0,0,0
BEGIN DESCRIPTION:
Elm 02 44 14.0
END DESCRIPTION:
XS GIS Cut Line= 3
      1591448.00      6876181.92      1592170.60      6876370.44
      1592640.88      6876674.69
#Sta/Elev= 30
  4090.9 1658.62  4125.4 1658.74  4175.0 1658.12  4284.2 1655.35  4323.2 1653.46
  4366.8 1651.80  4372.2 1651.08  4478.0 1648.79  4492.5 1648.47  4726.2 1644.40
  4790.6 1643.94  4860.8 1644.56  4969.6 1642.97  4975.6 1643.28  4985.7 1641.94
  4995.6 1639.63  4996.1 1639.13  5003.9 1639.13  5004.4 1639.63  5005.9 1640.58
  5021.1 1643.02  5027.0 1642.35  5069.2 1641.61  5099.6 1642.83  5105.5 1642.44
  5114.7 1643.10  5120.7 1642.32  5151.0 1644.78  5212.2 1644.65  5397.8 1644.78
#Mann=9,-1,0
  4090.9   0.035       0  4125.4   0.063       0  4323.2   0.035       0
  4478.0    0.07       0  4492.5   0.035       0  4985.7    0.07       0
  4995.6    0.07       0  5004.4    0.07       0  5212.2   0.035       0
Bank Sta=4995.6,5004.4
Exp/Cntr=0.3,0.1

Chan Stop Cuts=-1