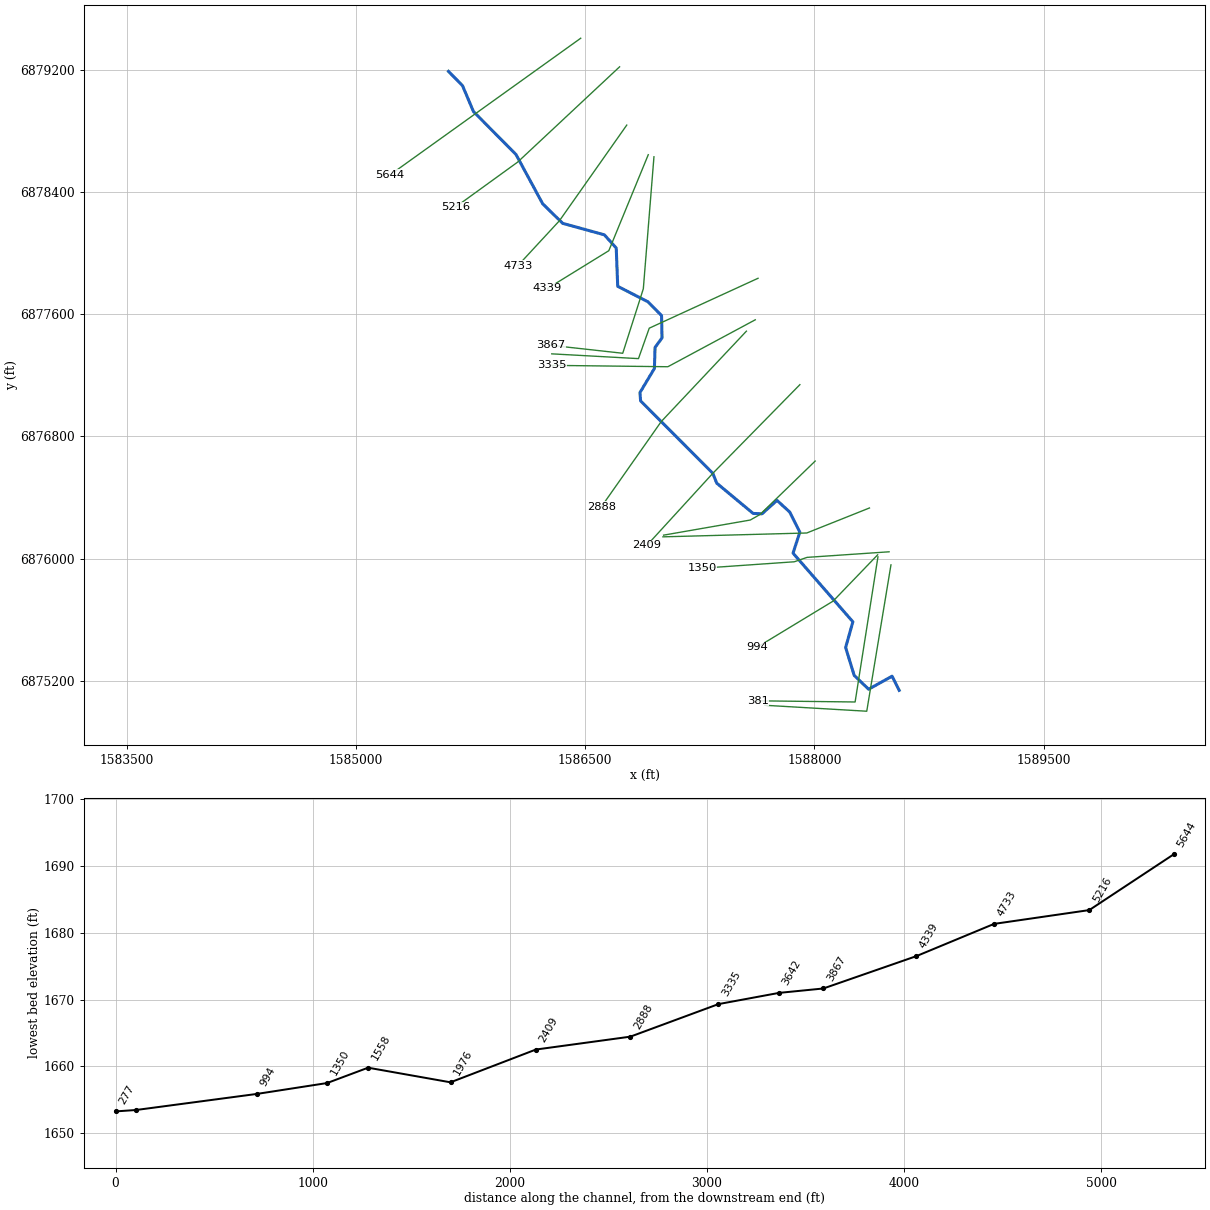
--- Elm 02 45.prj (project) ---

Proj Title=Elm 02 45 Base Level Engineering
Current Plan=p01
Default Exp/Contr=0.3,0.1
English Units
Geom File=g01
Flow File=f01
Plan File=p01
BEGIN DESCRIPTION:
Elm 02 45
END DESCRIPTION:

--- Elm 02 45.p01 (plan) ---

Plan Title=Multiple Run
Short Identifier=Multiple
Geom File=g01
Flow File=f01
Subcritical Flow
K Sum by GR= 0
Std Step Tol= 0.01
Critical Tol= 0.01
Num of Std Step Trials= 20
Max Error Tol= 0.3
Flow Tol Ratio= 0.001
Split Flow NTrial= 30
Split Flow Tol= 0.02
Split Flow Ratio= 0.02
Log Output Level= 0
Friction Slope Method= 1
Unsteady Friction Slope Method= 2
Unsteady Bridges Friction Slope Method= 1
Parabolic Critical Depth
Global Vel Dist=  1 , 1 , 1
Global Log Level= 0
CheckData=True
Encroach Param= -1, 0, 0, 0
BEGIN DESCRIPTION:
Multiple Run
END DESCRIPTION:

--- Elm 02 45.f01 (steady flow) ---

Flow Title=Multiple
Number of Profiles=7
Profile Names=10-year,25-year,50-year,1pct_min,100-year,1pct_plu,500-year
River Rch & RM= Elm 02 45,Reach-1,5644
     152     205     246     148     295     589     429
Boundary for River Rch & Prof#=Elm 02 45,Reach-1,1
Up Type=0
Dn Type=3
Dn Slope=0.005
Boundary for River Rch & Prof#=Elm 02 45,Reach-1,2
Up Type=0
Dn Type=3
Dn Slope=0.005
Boundary for River Rch & Prof#=Elm 02 45,Reach-1,3
Up Type=0
Dn Type=3
Dn Slope=0.005
Boundary for River Rch & Prof#=Elm 02 45,Reach-1,4
Up Type=0
Dn Type=3
Dn Slope=0.005
Boundary for River Rch & Prof#=Elm 02 45,Reach-1,5
Up Type=0
Dn Type=3
Dn Slope=0.005
Boundary for River Rch & Prof#=Elm 02 45,Reach-1,6
Up Type=0
Dn Type=3
Dn Slope=0.005
Boundary for River Rch & Prof#=Elm 02 45,Reach-1,7
Up Type=0
Dn Type=3
Dn Slope=0.005

--- Elm 02 45.g01 (geometry) ---

Geom Title=Existing Conditions

River Reach=Elm 02 45,Reach-1
Reach XY= 30
      1585605.00      6879188.00      1585696.91      6879094.08
      1585768.62      6878924.79      1586046.84      6878644.05
      1586221.64      6878321.32      1586352.57      6878193.52
      1586625.20      6878118.39      1586702.95      6878032.16
      1586712.69      6877781.52      1586911.07      6877679.87
      1586999.55      6877590.46      1587002.75      6877443.94
      1586957.27      6877382.06      1586952.75      6877243.93
      1586858.31      6877086.26      1586862.48      6877031.94
      1587335.14      6876557.92      1587360.62      6876493.62
      1587598.95      6876295.46      1587657.29      6876293.09
      1587755.02      6876380.92      1587838.36      6876304.75
      1587904.92      6876172.61      1587860.09      6876035.70
      1588251.87      6875586.37      1588204.41      6875417.95
      1588260.52      6875235.54      1588354.90      6875145.28
      1588508.61      6875230.52      1588555.00      6875138.00

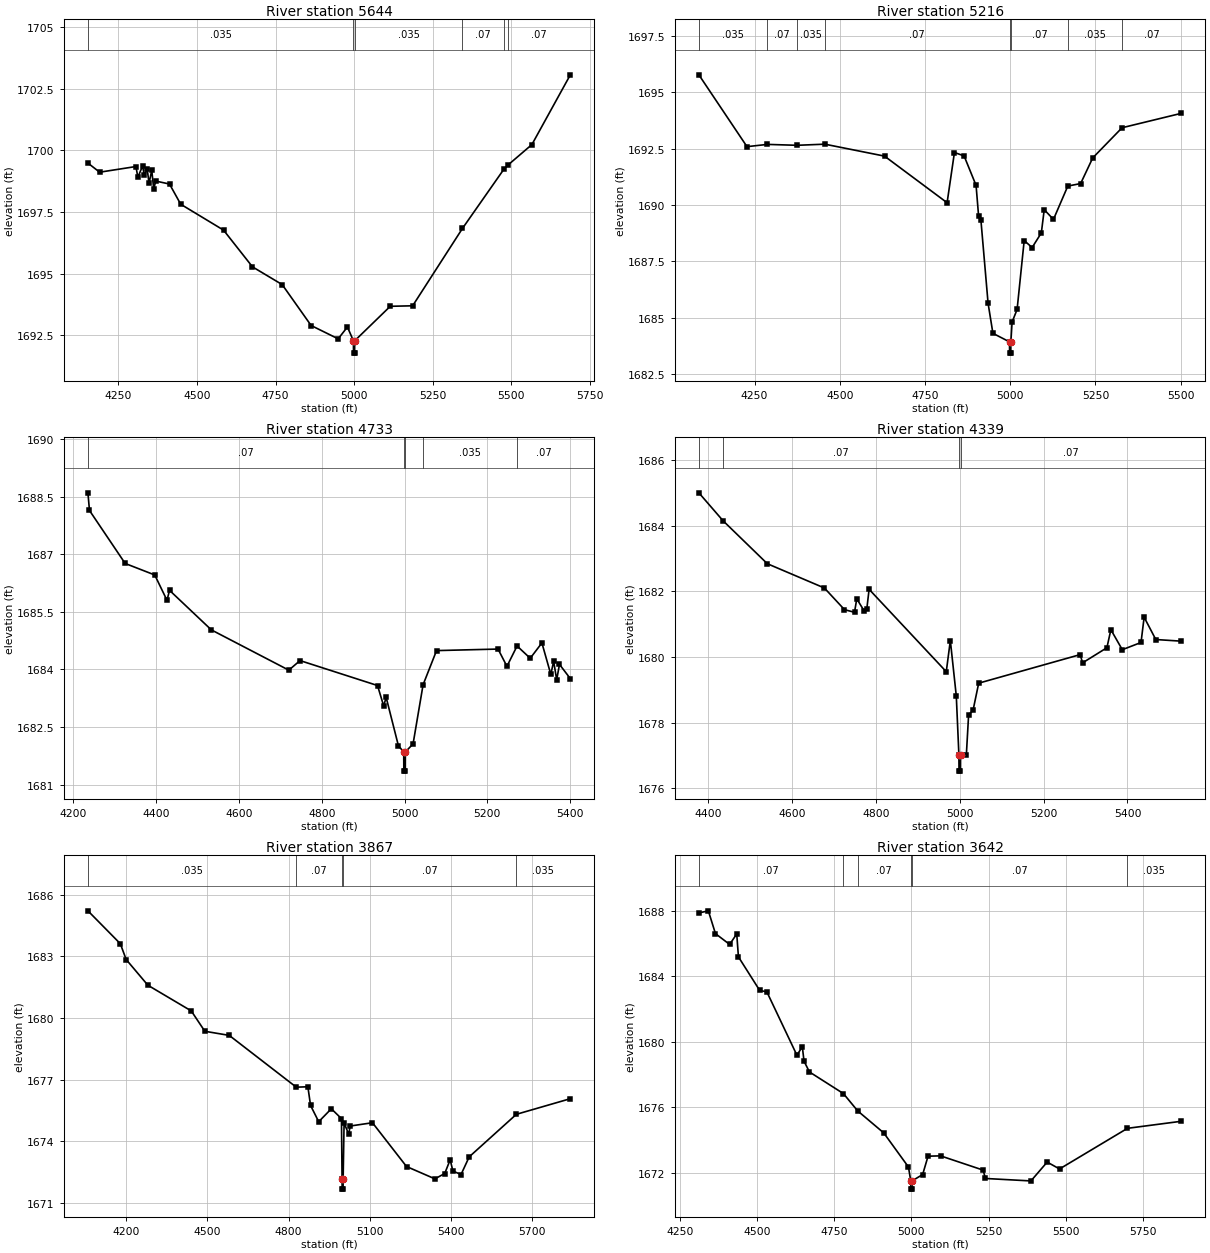
Type RM Length L Ch R = 1,5644,428,428,428
BEGIN DESCRIPTION:
Elm 02 45 11.0
END DESCRIPTION:
XS GIS Cut Line= 2
      1586470.54      6879404.71      1585222.34      6878510.42
#Sta/Elev= 30
  4152.9 1699.48  4190.3 1699.11  4305.8 1699.34  4311.9 1698.90  4326.7 1699.36
  4332.8 1698.98  4341.4 1699.25  4347.5 1698.66  4356.1 1699.19  4362.3 1698.43
  4368.8 1698.75  4412.6 1698.63  4448.3 1697.81  4584.6 1696.76  4676.7 1695.27
  4771.3 1694.55  4863.4 1692.89  4949.4 1692.35  4978.9 1692.83  4998.0 1692.27
  4998.3 1691.77  5001.8 1691.77  5002.0 1692.27  5115.2 1693.67  5186.5 1693.69
  5345.1 1696.83  5477.4 1699.24  5490.8 1699.41  5566.0 1700.23  5688.4 1703.06
#Mann=6,-1,0
  4152.9   0.035       0  4998.0   0.035       0  5002.0   0.035       0
  5345.1    0.07       0  5477.4   0.035       0  5490.8    0.07       0
Bank Sta=4998,5002
Exp/Cntr=0.3,0.1

Type RM Length L Ch R = 1,5216,483,483,483
BEGIN DESCRIPTION:
Elm 02 45 10.0
END DESCRIPTION:
XS GIS Cut Line= 3
      1586724.99      6879217.75      1586057.54      6878594.05
      1585650.73      6878299.76
#Sta/Elev= 30
  4086.5 1695.78  4227.7 1692.59  4287.8 1692.69  4374.5 1692.65  4456.1 1692.70
  4631.2 1692.17  4814.9 1690.10  4836.4 1692.33  4864.7 1692.18  4899.9 1690.87
  4907.2 1689.53  4914.1 1689.33  4935.1 1685.64  4949.3 1684.30  4998.0 1683.92
  4998.3 1683.42  5001.8 1683.42  5002.0 1683.92  5005.6 1684.80  5020.3 1685.36
  5041.1 1688.42  5064.4 1688.11  5091.4 1688.76  5099.9 1689.79  5127.0 1689.36
  5169.1 1690.84  5206.7 1690.95  5242.2 1692.09  5328.3 1693.43  5502.1 1694.07
#Mann=8,-1,0
  4086.5   0.035       0  4287.8    0.07       0  4374.5   0.035       0
  4456.1    0.07       0  4998.0    0.07       0  5002.0    0.07       0
  5169.1   0.035       0  5328.3    0.07       0
Bank Sta=4998,5002
Exp/Cntr=0.3,0.1

Type RM Length L Ch R = 1,4733,394,394,394
BEGIN DESCRIPTION:
Elm 02 45 9.0
END DESCRIPTION:
XS GIS Cut Line= 3
      1586771.95      6878836.47      1586331.48      6878210.87
      1586059.36      6877916.88
#Sta/Elev= 30
  4234.9 1688.60  4238.7 1688.14  4324.9 1686.76  4396.4 1686.46  4426.0 1685.80
  4432.1 1686.06  4533.1 1685.03  4720.4 1683.98  4747.4 1684.23  4934.7 1683.58
  4949.5 1683.05  4955.6 1683.27  4985.2 1682.01  4998.0 1681.85  4998.3 1681.35
  5001.8 1681.35  5002.0 1681.85  5020.6 1682.06  5044.8 1683.60  5077.3 1684.49
  5225.9 1684.53  5247.4 1684.08  5271.9 1684.61  5303.7 1684.29  5331.9 1684.69
  5353.4 1683.87  5360.3 1684.21  5367.6 1683.73  5374.4 1684.13  5400.6 1683.76
#Mann=5,-1,0
  4234.9    0.07       0  4998.0    0.07       0  5002.0    0.07       0
  5044.8   0.035       0  5271.9    0.07       0
Bank Sta=4998,5002
Exp/Cntr=0.3,0.1

Type RM Length L Ch R = 1,4339,472,472,472
BEGIN DESCRIPTION:
Elm 02 45 8.2
END DESCRIPTION:
XS GIS Cut Line= 3
      1586912.64      6878642.58      1586654.42      6878014.53
      1586253.24      6877767.32
#Sta/Elev= 30
  4378.0 1685.00  4435.6 1684.15  4541.2 1682.84  4677.3 1682.10  4725.2 1681.44
  4749.1 1681.36  4754.5 1681.77  4772.2 1681.40  4778.5 1681.47  4783.9 1682.06
  4967.9 1679.55  4977.6 1680.50  4991.8 1678.81  4998.0 1677.02  4998.3 1676.52
  5001.8 1676.52  5002.0 1677.02  5015.8 1677.02  5021.2 1678.24  5031.7 1678.37
  5045.2 1679.20  5287.1 1680.07  5293.0 1679.82  5350.9 1680.28  5360.4 1680.83
  5387.6 1680.22  5432.3 1680.44  5439.7 1681.21  5467.5 1680.53  5528.3 1680.48
#Mann=4,-1,0
  4378.0   0.035       0  4435.6    0.07       0  4998.0    0.07       0
  5002.0    0.07       0
Bank Sta=4998,5002
Exp/Cntr=0.3,0.1

Type RM Length L Ch R = 1,3867,225,225,225
BEGIN DESCRIPTION:
Elm 02 45 8.0
END DESCRIPTION:
XS GIS Cut Line= 4
      1586949.89      6878629.18      1586880.30      6877765.14
      1586745.52      6877343.40      1586273.10      6877395.72
#Sta/Elev= 30
  4057.7 1685.21  4177.6 1683.61  4199.3 1682.84  4279.6 1681.59  4440.1 1680.34
  4490.3 1679.35  4580.6 1679.15  4828.7 1676.63  4871.5 1676.65  4881.5 1675.74
  4911.6 1674.95  4958.3 1675.58  4995.8 1675.10  4998.0 1672.17  4998.3 1671.67
  5001.8 1671.67  5002.0 1672.17  5005.5 1674.89  5022.7 1674.34  5027.9 1674.74
  5110.5 1674.90  5236.5 1672.77  5341.5 1672.17  5377.9 1672.43  5398.0 1673.10
  5408.1 1672.55  5438.2 1672.38  5468.4 1673.24  5642.9 1675.31  5842.6 1676.07
#Mann=5,-1,0
  4057.7   0.035       0  4828.7    0.07       0  4998.0    0.07       0
  5002.0    0.07       0  5642.9   0.035       0
Bank Sta=4998,5002
Exp/Cntr=0.3,0.1

Type RM Length L Ch R = 1,3642,307,307,307
BEGIN DESCRIPTION:
Elm 02 45 7.3
END DESCRIPTION:
XS GIS Cut Line= 4
      1587631.38      6877834.21      1586919.07      6877507.57
      1586848.51      6877308.42      1586281.08      6877339.61
#Sta/Elev= 30
  4311.4 1687.86  4342.1 1687.99  4365.1 1686.60  4411.1 1685.94  4434.1 1686.58
  4439.6 1685.18  4508.6 1683.13  4531.6 1683.05  4629.1 1679.18  4646.6 1679.70
  4652.1 1678.82  4669.6 1678.16  4779.7 1676.84  4826.2 1675.78  4910.5 1674.44
  4990.5 1672.36  4998.0 1671.51  4998.3 1671.01  5001.8 1671.01  5002.0 1671.51
  5036.5 1671.90  5054.0 1673.02  5094.5 1673.04  5232.5 1672.17  5239.9 1671.66
  5387.4 1671.51  5440.0 1672.66  5480.1 1672.24  5700.2 1674.72  5874.6 1675.15
#Mann=6,-1,0
  4311.4    0.07       0  4779.7   0.035       0  4826.2    0.07       0
  4998.0    0.07       0  5002.0    0.07       0  5700.2   0.035       0
Bank Sta=4998,5002
Exp/Cntr=0.3,0.1

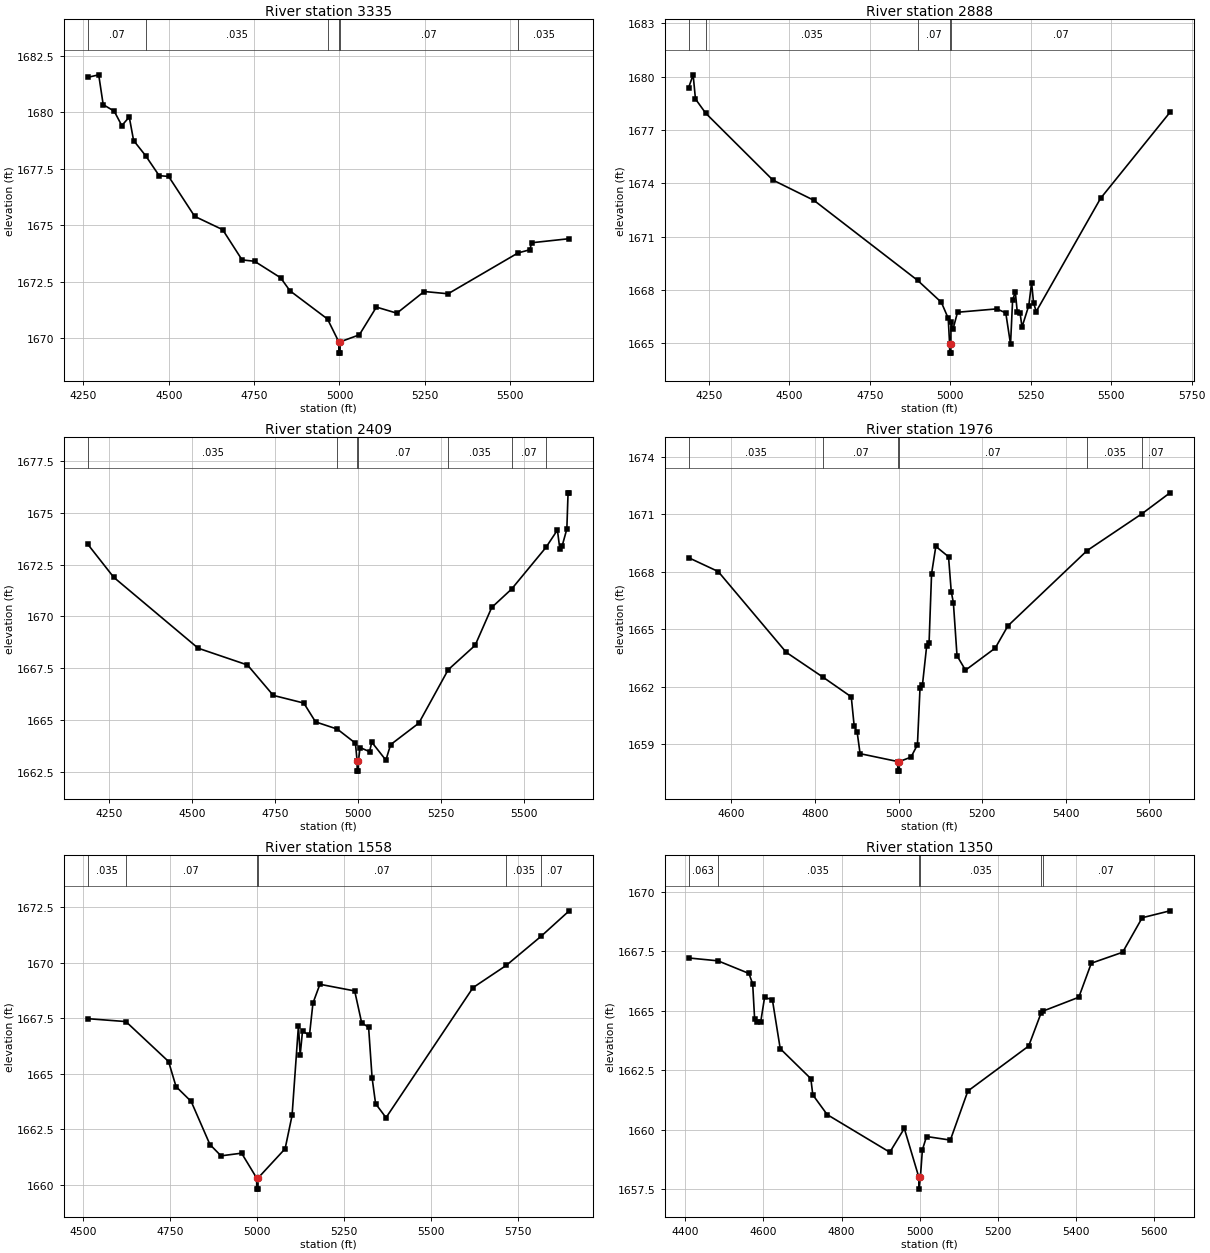
Type RM Length L Ch R = 1,3335,447,447,447
BEGIN DESCRIPTION:
Elm 02 45 7.0
END DESCRIPTION:
XS GIS Cut Line= 3
      1587613.03      6877562.42      1587041.02      6877255.33
      1586280.21      6877264.30
#Sta/Elev= 30
  4262.9 1681.55  4294.7 1681.66  4307.8 1680.34  4340.1 1680.05  4362.3 1679.41
  4384.2 1679.79  4396.9 1678.75  4432.0 1678.08  4471.9 1677.19  4499.5 1677.16
  4575.8 1675.39  4657.8 1674.80  4714.7 1673.46  4751.2 1673.40  4827.5 1672.67
  4855.1 1672.09  4965.0 1670.84  4998.0 1669.83  4998.3 1669.33  5001.8 1669.33
  5002.0 1669.83  5058.2 1670.14  5108.2 1671.37  5168.2 1671.10  5248.2 1672.06
  5318.2 1671.96  5523.2 1673.77  5557.9 1673.91  5562.9 1674.22  5673.0 1674.40
#Mann=6,-1,0
  4262.9    0.07       0  4432.0   0.035       0  4965.0    0.07       0
  4998.0    0.07       0  5002.0    0.07       0  5523.2   0.035       0
Bank Sta=4998,5002
Exp/Cntr=0.3,0.1

Type RM Length L Ch R = 1,2888,479,479,479
BEGIN DESCRIPTION:
Elm 02 45 6.0
END DESCRIPTION:
XS GIS Cut Line= 3
      1587555.00      6877488.00      1586997.53      6876896.51
      1586605.03      6876338.04
#Sta/Elev= 30
  4187.2 1679.39  4201.2 1680.11  4208.4 1678.75  4240.3 1677.95  4448.8 1674.19
  4576.2 1673.05  4898.9 1668.54  4972.3 1667.31  4993.7 1666.41  4998.0 1664.95
  4998.3 1664.45  5001.8 1664.45  5002.0 1664.95  5002.1 1666.20  5008.7 1665.81
  5022.6 1666.75  5144.8 1666.94  5172.5 1666.71  5187.3 1664.95  5193.7 1667.43
  5202.1 1667.90  5208.2 1666.76  5216.9 1666.70  5223.0 1665.92  5244.0 1667.13
  5252.7 1668.41  5258.8 1667.28  5267.1 1666.79  5467.0 1673.16  5682.6 1678.00
#Mann=5,-1,0
  4187.2    0.07       0  4240.3   0.035       0  4898.9    0.07       0
  4998.0    0.07       0  5002.0    0.07       0
Bank Sta=4998,5002
Exp/Cntr=0.3,0.1

Type RM Length L Ch R = 1,2409,433,433,433
BEGIN DESCRIPTION:
Elm 02 45 5.0
END DESCRIPTION:
XS GIS Cut Line= 3
      1587905.03      6877138.03      1587335.14      6876557.92
      1586904.97      6876087.97
#Sta/Elev= 30
  4186.8 1673.48  4264.6 1671.89  4519.2 1668.46  4667.7 1667.65  4745.5 1666.18
  4837.4 1665.81  4872.8 1664.90  4938.5 1664.55  4993.0 1663.87  4998.0 1663.02
  4998.3 1662.52  5001.8 1662.52  5002.0 1663.02  5007.1 1663.66  5035.5 1663.46
  5042.3 1663.92  5084.8 1663.05  5099.0 1663.80  5184.1 1664.84  5272.5 1667.42
  5353.7 1668.60  5403.7 1670.43  5463.6 1671.32  5567.0 1673.33  5601.6 1674.17
  5609.0 1673.24  5615.8 1673.40  5630.0 1674.22  5633.7 1675.97  5637.1 1675.97
#Mann=7,-1,0
  4186.8   0.035       0  4938.5    0.07       0  4998.0    0.07       0
  5002.0    0.07       0  5272.5   0.035       0  5463.6    0.07       0
  5567.0   0.035       0
Bank Sta=4998,5002
Exp/Cntr=0.3,0.1

Type RM Length L Ch R = 1,1976,418,418,418
BEGIN DESCRIPTION:
Elm 02 45 4.0
END DESCRIPTION:
XS GIS Cut Line= 4
      1588005.03      6876638.03      1587644.36      6876288.56
      1587580.15      6876252.23      1587013.08      6876153.35
#Sta/Elev= 30
  4497.8 1668.73  4568.5 1668.01  4731.3 1663.80  4820.3 1662.49  4886.9 1661.48
  4893.9 1659.95  4901.0 1659.64  4908.0 1658.52  4998.0 1658.11  4998.3 1657.61
  5001.8 1657.61  5002.0 1658.11  5029.8 1658.34  5045.2 1658.98  5051.4 1661.94
  5057.2 1662.10  5067.3 1664.13  5073.0 1664.26  5079.0 1667.89  5089.2 1669.32
  5119.6 1668.78  5126.1 1666.96  5131.2 1666.39  5139.9 1663.62  5160.2 1662.87
  5231.3 1664.02  5261.7 1665.18  5451.1 1669.10  5583.0 1671.03  5649.4 1672.11
#Mann=6,-1,0
  4497.8   0.035       0  4820.3    0.07       0  4998.0    0.07       0
  5002.0    0.07       0  5451.1   0.035       0  5583.0    0.07       0
Bank Sta=4998,5002
Exp/Cntr=0.3,0.1

Type RM Length L Ch R = 1,1558,208,208,208
BEGIN DESCRIPTION:
Elm 02 45 3.0
END DESCRIPTION:
XS GIS Cut Line= 3
      1588360.48      6876331.15      1587950.02      6876167.46
      1587008.65      6876142.28
#Sta/Elev= 30
  4512.8 1667.48  4622.1 1667.35  4744.8 1665.55  4766.3 1664.42  4809.8 1663.75
  4863.7 1661.81  4895.5 1661.30  4954.7 1661.42  4998.0 1660.30  4998.3 1659.80
  5001.8 1659.80  5002.0 1660.30  5079.8 1661.62  5099.8 1663.12  5118.1 1667.16
  5123.1 1665.84  5129.8 1666.92  5149.8 1666.73  5159.8 1668.18  5179.8 1669.03
  5279.8 1668.73  5299.8 1667.30  5319.8 1667.09  5329.8 1664.82  5339.9 1663.65
  5369.9 1663.02  5620.0 1668.88  5715.4 1669.88  5815.4 1671.19  5896.4 1672.34
#Mann=6,-1,0
  4512.8   0.035       0  4622.1    0.07       0  4998.0    0.07       0
  5002.0    0.07       0  5715.4   0.035       0  5815.4    0.07       0
Bank Sta=4998,5002
Exp/Cntr=0.3,0.1

Type RM Length L Ch R = 1,1350,356,356,356
BEGIN DESCRIPTION:
Elm 02 45 2.2
END DESCRIPTION:
XS GIS Cut Line= 4
      1588488.94      6876044.45      1587951.55      6876007.90
      1587868.72      6875979.13      1587264.10      6875936.98
#Sta/Elev= 30
  4408.6 1667.21  4483.7 1667.09  4562.9 1666.56  4572.6 1666.12  4577.6 1664.63
  4582.9 1664.54  4593.0 1664.51  4603.0 1665.55  4623.0 1665.46  4643.1 1663.40
  4721.5 1662.14  4726.5 1661.46  4763.4 1660.63  4923.7 1659.05  4960.8 1660.05
  4998.0 1658.00  4998.3 1657.50  5002.0 1658.00  5007.1 1659.15  5017.7 1659.71
  5078.7 1659.56  5123.5 1661.62  5279.2 1663.51  5311.3 1664.91  5314.7 1664.97
  5407.6 1665.56  5439.6 1666.99  5519.8 1667.45  5569.9 1668.90  5641.0 1669.19
#Mann=6,-1,0
  4408.6   0.063       0  4483.7   0.035       0  4998.0   0.035       0
  5002.0   0.035       0  5311.3   0.045       0  5314.7    0.07       0
Bank Sta=4998,5002
Exp/Cntr=0.3,0.1

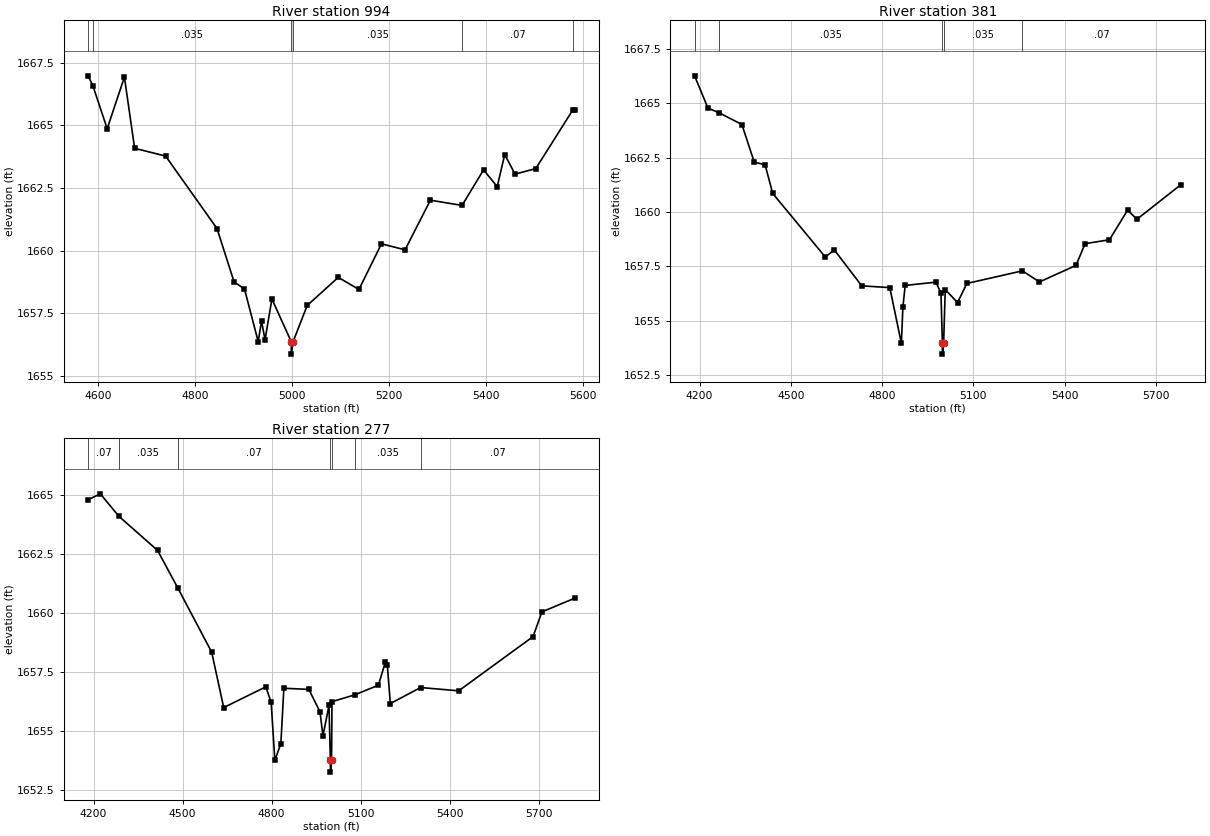
Type RM Length L Ch R = 1,994,613,613,613
BEGIN DESCRIPTION:
Elm 02 45 2.0
END DESCRIPTION:
XS GIS Cut Line= 3
      1588414.06      6876024.61      1588122.38      6875721.58
      1587624.47      6875419.64
#Sta/Elev= 30
  4579.4 1666.97  4589.3 1666.57  4618.7 1664.86  4654.2 1666.92  4675.3 1664.08
  4739.1 1663.77  4845.1 1660.88  4880.3 1658.75  4901.7 1658.47  4930.0 1656.37
  4936.9 1657.19  4944.1 1656.44  4958.3 1658.07  4998.0 1656.37  4998.3 1655.87
  5002.0 1656.37  5031.0 1657.81  5095.0 1658.93  5137.7 1658.45  5184.1 1660.27
  5232.7 1660.03  5285.0 1662.01  5350.2 1661.80  5394.6 1663.22  5422.7 1662.55
  5438.2 1663.83  5459.5 1663.05  5502.2 1663.27  5578.9 1665.62  5582.3 1665.59
#Mann=6,-1,0
  4579.4   0.063       0  4589.3   0.035       0  4998.0   0.035       0
  5002.0   0.035       0  5350.2    0.07       0  5578.9   0.045       0
Bank Sta=4998,5002
Exp/Cntr=0.3,0.1

Type RM Length L Ch R = 1,381,104,104,104
BEGIN DESCRIPTION:
Elm 02 45 1.2
END DESCRIPTION:
XS GIS Cut Line= 3
      1588416.07      6876011.57      1588266.53      6875061.77
      1587629.58      6875069.36
#Sta/Elev= 30
  4183.8 1666.26  4227.9 1664.77  4263.3 1664.57  4339.3 1664.02  4379.8 1662.29
  4415.5 1662.17  4440.5 1660.85  4613.1 1657.93  4643.0 1658.25  4733.1 1656.60
  4825.2 1656.52  4863.2 1653.96  4868.3 1655.64  4875.8 1656.62  4977.0 1656.77
  4993.3 1656.26  4998.0 1653.96  4998.3 1653.46  5002.0 1653.96  5007.4 1656.43
  5047.9 1655.83  5078.3 1656.71  5260.9 1657.29  5316.8 1656.78  5436.9 1657.54
  5466.9 1658.54  5546.9 1658.72  5606.9 1660.09  5636.9 1659.66  5782.3 1661.26
#Mann=5,-1,0
  4183.8   0.063       0  4263.3   0.035       0  4998.0   0.035       0
  5002.0   0.035       0  5260.9    0.07       0
Bank Sta=4998,5002
Exp/Cntr=0.3,0.1

Type RM Length L Ch R = 1,277,0,0,0
BEGIN DESCRIPTION:
Elm 02 45 1.0
END DESCRIPTION:
XS GIS Cut Line= 3
      1588501.14      6875958.78      1588342.71      6875001.24
      1587675.01      6875040.31
#Sta/Elev= 30
  4181.7 1664.81  4223.0 1665.06  4285.1 1664.11  4415.6 1662.66  4483.7 1661.07
  4598.1 1658.34  4638.6 1655.99  4780.5 1656.87  4798.5 1656.21  4810.9 1653.75
  4831.2 1654.46  4841.3 1656.81  4925.6 1656.76  4963.0 1655.81  4973.1 1654.79
  4993.4 1656.08  4998.0 1653.75  4998.3 1653.25  5002.0 1653.75  5003.5 1656.24
  5080.5 1656.53  5160.0 1656.94  5183.7 1657.94  5190.0 1657.79  5200.0 1656.16
  5302.3 1656.84  5430.4 1656.70  5680.9 1659.00  5710.9 1660.05  5821.1 1660.63
#Mann=7,-1,0
  4181.7    0.07       0  4285.1   0.035       0  4483.7    0.07       0
  4998.0    0.07       0  5002.0    0.07       0  5080.5   0.035       0
  5302.3    0.07       0
Bank Sta=4998,5002
Exp/Cntr=0.3,0.1

Chan Stop Cuts=-1