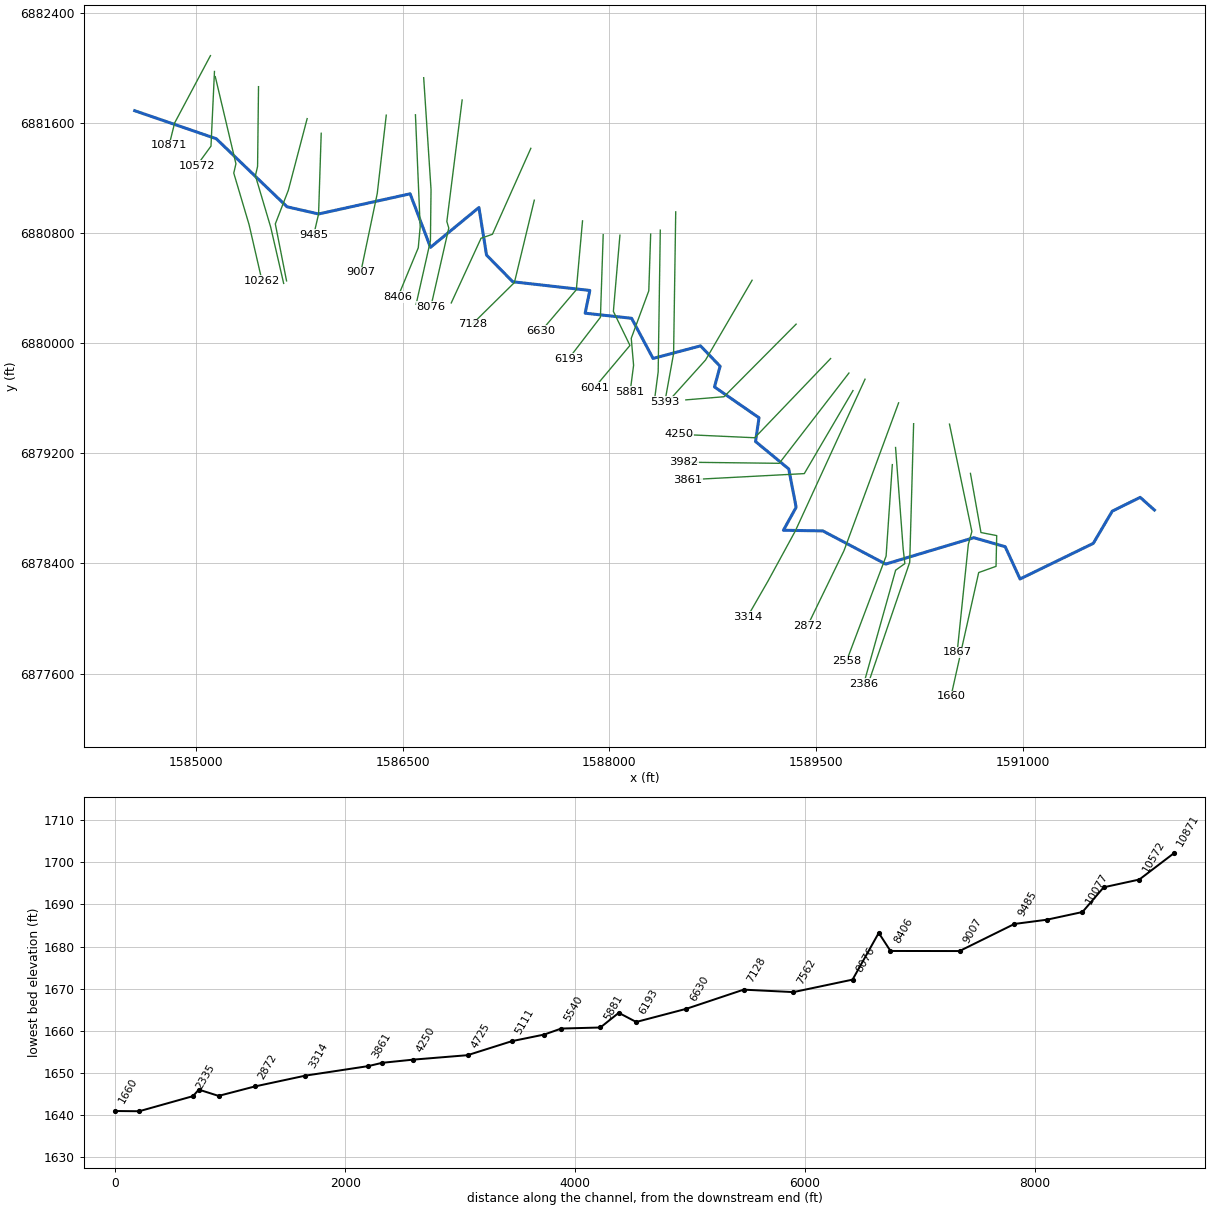
--- Elm 02 46.prj (project) ---

Proj Title=Elm 02 46 Base Level Engineering
Current Plan=p01
Default Exp/Contr=0.3,0.1
English Units
Geom File=g01
Flow File=f01
Plan File=p01
Y Axis Title=Elevation
X Axis Title(PF)=Main Channel Distance
X Axis Title(XS)=Station
BEGIN DESCRIPTION:
Elm 02 46
END DESCRIPTION:
DSS Export Rating Curves= 0
DSS Export Rating Curve Sorted= 0
DSS Export Volume Flow Curves= 0
DXF OffsetX= 0
DXF OffsetY= 0
DXF ScaleX= 1
DXF ScaleY= 10

--- Elm 02 46.p01 (plan) ---

Plan Title=Multiple Run
Program Version=4.10
Short Identifier=Multiple
Geom File=g01
Flow File=f01
Subcritical Flow
K Sum by GR= 0
Std Step Tol= 0.01
Critical Tol= 0.01
Num of Std Step Trials= 20
Max Error Tol= 0.3
Flow Tol Ratio= 0.001
Split Flow NTrial= 30
Split Flow Tol= 0.02
Split Flow Ratio= 0.02
Log Output Level= 0
Friction Slope Method= 1
Unsteady Friction Slope Method= 2
Unsteady Bridges Friction Slope Method= 1
Parabolic Critical Depth
Global Vel Dist= 1 , 1 , 1
Global Log Level= 0
CheckData=True
Encroach Param=-1 ,0,0, 0
BEGIN DESCRIPTION:
Multiple Run
END DESCRIPTION:
Computation Interval=1HOUR
Output Interval=1HOUR
Run HTab= 0
Run UNet= 0
Run PostProcess= 0
Run WQNet= 0
UNET Theta= 1
UNET Theta Warmup= 1
UNET ZTol= 0.02
UNET ZSATol= 0.05
UNET MxIter= 20
UNET MaxInSteps= 0
UNET DtIC= 0
UNET DtMin= 0
UNET MaxCRTS= 20
UNET WFStab= 2
UNET SFStab= 1
UNET WFX= 1
UNET SFX= 1
UNET DSS MLevel= 4
UNET DZMax Abort= 100
UNET Convert EG Bridges= 0
UNET Use Existing IB Tables=-1
UNET Froude Reduction=False
UNET Froude Limit= 1
UNET Froude Power= 10
UNET Time Slicing=0,0, 5
UNET Junction Losses=0
Instantaneous Interval=1HOUR
Write IC File= 0
Write IC File at Sim End=0
Echo Input=False
Echo Parameters=False
Echo Output=False
Write Detailed= 0
WQ AD Non Conservative
WQ ULTIMATE=-1
WQ Max Comp Step=1HOUR
WQ Output Interval=15MIN
WQ Output Selected Increments= 0
WQ Output face flow=0
WQ Output face velocity=0
WQ Output face area=0
WQ Output face dispersion=0
WQ Output cell volume=0
WQ Output cell surface area=0
WQ Output cell continuity=0
WQ Output cumulative cell continuity=0
WQ Output face conc=0
WQ Output face dconc_dx=0
WQ Output face courant=0
WQ Output face peclet=0
WQ Output face adv mass=0
WQ Output face disp mass=0
WQ Output cell mass=0
WQ Output cell source sink temp=0
WQ Output cell source sink nsm=0
WQ Output MaxMinRange=-1
WQ Daily Max Min Mean=-1
WQ Daily Range=0
WQ Daily Time=0
WQ Create Restart=0
WQ Fixed Restart=0
WQ System Summary=0
WQ Use Fixed Temperature=0
Sorting and Armoring Iterations= 10
XS Update Threshold= 0.02
Hydraulics Update Threshold= 0.02
Energy Slope Method= 1
Volume Change Method= 0
XS Weighting Method= 0
Number of US Weighted Cross Sections= 1
Number of DS Weighted Cross Sections= 1
Upstream XS Weight=0.25
Main XS Weight=0.5
Downstream XS Weight=0.25
Number of DS XS's Weighted with US Boundary= 1
Upstream Boundary Weight= 1
Weight of XSs Associated with US Boundary= 0
Number of US XS's Weighted with DS Boundary= 1
Downstream Boundary Weight= 0.5
Weight of XSs Associated with DS Boundary= 0.5
Sediment Output Level= 4
Mass or Volume Output= 0
Output Increment Type= 1
Profile and TS Output Increment= 10
XS Output Flag= 0
XS Output Increment= 10
Disregard all LS=0
Disregard all Conn=0
Disregard all Breaches=0
Disregard all Pumps=0

--- Elm 02 46.f01 (steady flow) ---

Flow Title=Multiple
Number of Profiles=7
Profile Names=10-year,25-year,50-year,1pct_min,100-year,1pct_plu,500-year
River Rch & RM= Elm 02 46,Reach-1,10871
     215     296     361     220     439     876     657
River Rch & RM= Elm 02 46,Reach-1,473
     243     337     413     253     504    1006     761
Boundary for River Rch & Prof#=Elm 02 46,Reach-1,1
Up Type=0
Dn Type=3
Dn Slope=0.005
Boundary for River Rch & Prof#=Elm 02 46,Reach-1,2
Up Type=0
Dn Type=3
Dn Slope=0.005
Boundary for River Rch & Prof#=Elm 02 46,Reach-1,3
Up Type=0
Dn Type=3
Dn Slope=0.005
Boundary for River Rch & Prof#=Elm 02 46,Reach-1,4
Up Type=0
Dn Type=3
Dn Slope=0.005
Boundary for River Rch & Prof#=Elm 02 46,Reach-1,5
Up Type=0
Dn Type=3
Dn Slope=0.005
Boundary for River Rch & Prof#=Elm 02 46,Reach-1,6
Up Type=0
Dn Type=3
Dn Slope=0.005
Boundary for River Rch & Prof#=Elm 02 46,Reach-1,7
Up Type=0
Dn Type=3
Dn Slope=0.005

--- Elm 02 46.g01 (geometry) ---

Geom Title=Existing Conditions
Program Version=4.10

River Reach=Elm 02 46       ,Reach-1
Reach XY= 30
        1584555.        6881688.      1585146.85      6881484.62
      1585660.85      6880990.06      1585889.61      6880938.09
      1586554.01      6881084.47      1586701.66      6880695.58
      1587053.27      6880985.08      1587108.53      6880639.45
      1587298.54      6880445.74      1587858.02      6880382.54
      1587824.01      6880217.52      1588161.06      6880180.52
      1588316.69      6879888.99      1588661.19      6879980.19
      1588803.38      6879831.97      1588762.48      6879681.93
      1589085.71      6879458.04      1589060.39      6879285.56
      1589301.39      6879086.52      1589355.06      6878807.99
      1589262.55      6878641.16      1589548.96      6878636.38
        1590005.       6878395.5      1590644.31      6878587.23
      1590872.15      6878521.72      1590979.82      6878287.41
      1591511.38      6878545.99      1591648.92      6878779.91
      1591851.77      6878880.23        1591955.        6878788.

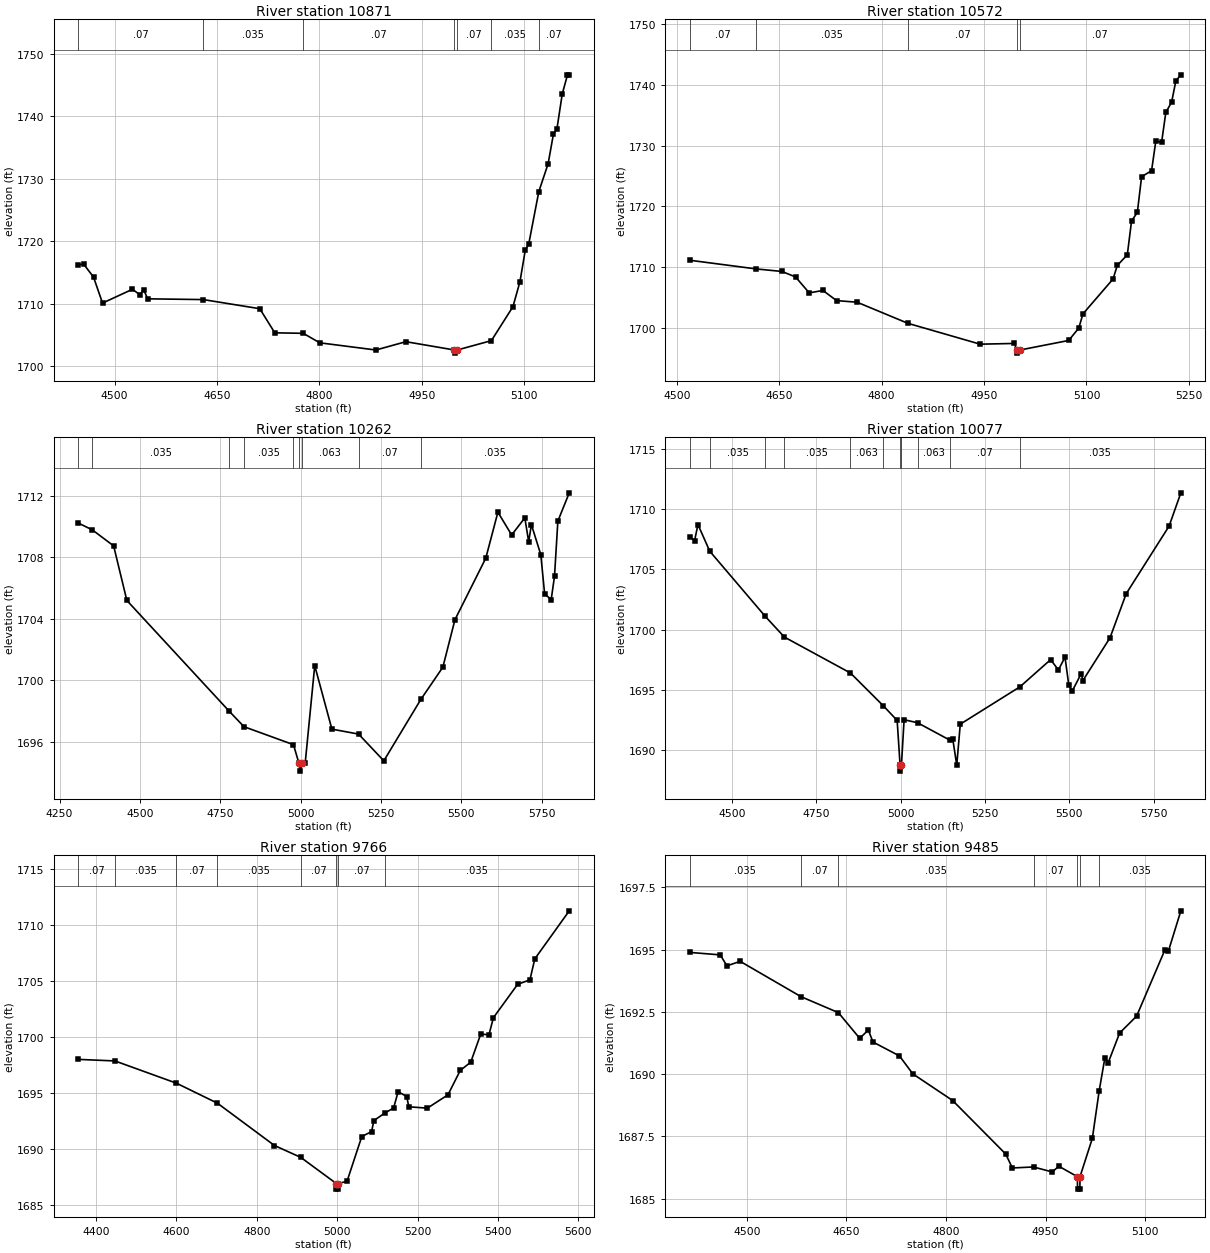
Type RM Length L Ch R = 1 ,10871   ,299,299,299
BEGIN DESCRIPTION:
Elm 02 46 22.0
END DESCRIPTION:
XS GIS Cut Line= 3
      1585104.99      6882087.98      1584845.21      6881599.23
      1584804.99      6881437.97
#Sta/Elev= 30
  4446.5 1716.24  4454.6 1716.37  4469.1 1714.29  4482.3 1710.13  4526.2 1712.34
  4536.9 1711.46  4542.5 1712.29  4548.4 1710.81  4629.9 1710.69  4712.7 1709.23
  4734.7 1705.37  4776.4 1705.29  4800.6 1703.77  4882.9 1702.62  4926.8 1703.95
    4998 1702.62  4998.3 1702.12    5002 1702.62  5052.1 1704.12  5083.7 1709.56
    5094 1713.58  5101.7 1718.58  5106.8 1719.58  5121.6 1727.98  5135.2 1732.42
    5143 1737.17  5148.1 1737.98  5155.9 1743.59  5163.6 1746.66  5166.2 1746.66
#Mann= 7 ,-1 , 0
  4446.5     .07       0  4629.9    .035       0  4776.4     .07       0
    4998     .07       0    5002     .07       0  5052.1    .035       0
  5121.6     .07       0
Bank Sta=4998,5002
XS Rating Curve= 0 ,0
Exp/Cntr=0.3,0.1

Type RM Length L Ch R = 1 ,10572   ,310,310,310
BEGIN DESCRIPTION:
Elm 02 46 21.0
END DESCRIPTION:
XS GIS Cut Line= 3
      1585134.19      6881972.85      1585108.89      6881430.81
      1585005.02      6881288.03
#Sta/Elev= 30
    4519 1711.17  4616.6 1709.74    4654 1709.33    4674 1708.43    4694 1705.81
  4714.1 1706.21  4734.1 1704.54  4764.1 1704.28  4838.6 1700.81  4944.3 1697.39
  4994.4 1697.51    4998 1696.42  4998.3 1695.92    5002 1696.42    5074    1698
  5088.7 1700.03  5094.9 1702.37  5138.9 1708.09  5145.1 1710.31  5159.8 1712.07
    5166 1717.61  5174.5 1719.03  5180.7 1724.89  5195.3 1725.86  5201.5 1730.71
    5210 1730.52  5216.2 1735.44  5224.7 1737.14  5230.9 1740.63  5238.2 1741.61
#Mann= 5 ,-1 , 0
    4519     .07       0  4616.6    .035       0  4838.6     .07       0
    4998     .07       0    5002     .07       0
Bank Sta=4998,5002
XS Rating Curve= 0 ,0
Exp/Cntr=0.3,0.1

Type RM Length L Ch R = 1 ,10262   ,185,185,185
BEGIN DESCRIPTION:
Elm 02 46 20.5
END DESCRIPTION:
XS GIS Cut Line= 5
      1585140.04      6881935.63      1585289.87      6881302.37
      1585274.13      6881235.13      1585385.33      6880860.45
      1585479.09      6880453.23
#Sta/Elev= 30
  4307.6 1710.22  4351.9 1709.77  4418.2 1708.73  4459.3 1705.18  4777.7 1697.98
  4823.8 1696.97  4977.8  1695.8    4995 1694.58  4998.3 1694.08    5005 1694.58
  5014.2 1694.58    5044 1700.94  5097.4 1696.81  5180.4 1696.49    5259 1694.75
  5374.1 1698.74  5442.7 1700.84  5480.4 1703.93  5576.3 1707.93    5614 1710.92
  5656.8 1709.44  5697.8 1710.55  5709.8    1709  5718.3 1710.11  5747.5 1708.16
  5759.4 1705.61  5779.9 1705.24  5790.2 1706.76  5800.6 1710.34  5836.1 1712.18
#Mann= 9 ,-1 , 0
  4307.6     .07       0  4351.9    .035       0  4777.7     .07       0
  4823.8    .035       0  4977.8    .063       0    4995    .063       0
    5005    .063       0  5180.4     .07       0  5374.1    .035       0
#XS Ineff= 2 , 0
       0                    5044       0    1698
Permanent Ineff=
       F       F
Bank Sta=4995,5005
XS Rating Curve= 0 ,0
Exp/Cntr=0.3,0.1

Type RM Length L Ch R = 1 ,10077   ,311,311,311
BEGIN DESCRIPTION:
Elm 02 46 20.3
END DESCRIPTION:
XS GIS Cut Line= 5
      1585453.82      6881862.54      1585446.97      6881283.18
      1585431.23      6881215.93      1585542.43      6880841.25
       1585636.2        6880434.
#Sta/Elev= 30
  4373.8 1707.72  4388.3  1707.4  4398.3 1708.74  4433.3 1706.52  4597.8  1701.1
  4654.8 1699.37  4850.7 1696.38  4948.6 1693.64  4989.3 1692.43    4998 1688.71
  4998.3 1688.21    5002 1688.71  5009.9 1692.49  5049.7 1692.24  5145.6 1690.79
  5154.5 1690.85  5166.1 1688.71  5176.6 1692.12  5353.6 1695.23  5444.5 1697.49
  5467.7 1696.64  5487.3  1697.7  5498.5 1695.37  5508.8 1694.88  5535.2 1696.32
  5540.3 1695.75  5620.8 1699.31  5668.8 1702.98  5796.1 1708.61    5831 1711.38
#Mann= 11 ,-1 , 0
  4373.8     .07       0  4433.3    .035       0  4597.8     .07       0
  4654.8    .035       0  4850.7    .063       0  4948.6    .035       0
    4998    .035       0    5002    .035       0  5049.7    .063       0
  5145.6     .07       0  5353.6    .035       0
Bank Sta=4998,5002
XS Rating Curve= 0 ,0
Exp/Cntr=0.3,0.1

Type RM Length L Ch R = 1 ,9766    ,281,281,281
BEGIN DESCRIPTION:
Elm 02 46 20.0
END DESCRIPTION:
XS GIS Cut Line= 4
      1585806.75      6881630.32      1585670.21      6881110.41
      1585575.74       6880865.9       1585657.2      6880452.01
#Sta/Elev= 30
  4355.8 1697.98  4447.4 1697.84  4600.4 1695.85  4702.4 1694.06  4844.1 1690.28
  4909.5 1689.22    4998 1686.88  4998.3 1686.38  5001.8 1686.38    5002 1686.88
  5024.6 1687.08  5061.3 1691.08  5085.8 1691.53  5091.2  1692.5  5118.9 1693.19
  5140.4 1693.63  5151.7 1695.09  5173.1 1694.66  5178.2 1693.74  5224.4 1693.62
  5275.6 1694.81  5306.2 1696.99  5332.3 1697.73  5357.2 1700.25  5377.5 1700.17
  5388.7 1701.71  5448.9 1704.69  5479.5 1705.09  5491.5 1706.96  5577.3 1711.26
#Mann= 8 ,-1 , 0
  4355.8     .07       0  4447.4    .035       0  4600.4     .07       0
  4702.4    .035       0  4909.5     .07       0    4998     .07       0
    5002     .07       0  5118.9    .035       0
Bank Sta=4998,5002
XS Rating Curve= 0 ,0
Exp/Cntr=0.3,0.1

Type RM Length L Ch R = 1 ,9485    ,478,478,478
BEGIN DESCRIPTION:
Elm 02 46 19.0
END DESCRIPTION:
XS GIS Cut Line= 3
      1585908.72      6881524.08      1585889.61      6880938.09
      1585855.01      6880788.03
#Sta/Elev= 30
  4413.7 1694.89  4459.8 1694.79  4469.8 1694.35  4489.8 1694.53  4581.6 1693.11
  4637.8 1692.47  4669.9 1691.44    4683 1691.77  4689.9 1691.29  4729.9 1690.73
    4750 1690.01    4810 1688.94    4890 1686.79    4900 1686.23  4931.9 1686.27
  4960.1 1686.07  4970.1  1686.3    4998 1685.88  4998.3 1685.38  5001.8 1685.38
    5002 1685.88  5020.6 1687.42  5030.9 1689.33  5039.4 1690.64  5044.5 1690.46
  5061.7 1691.65  5087.3 1692.33  5130.1    1695  5135.2 1694.94    5154 1696.56
#Mann= 7 ,-1 , 0
  4413.7    .035       0  4581.6     .07       0  4637.8    .035       0
  4931.9     .07       0    4998     .07       0    5002     .07       0
  5030.9    .035       0
Bank Sta=4998,5002
XS Rating Curve= 0 ,0
Exp/Cntr=0.3,0.1

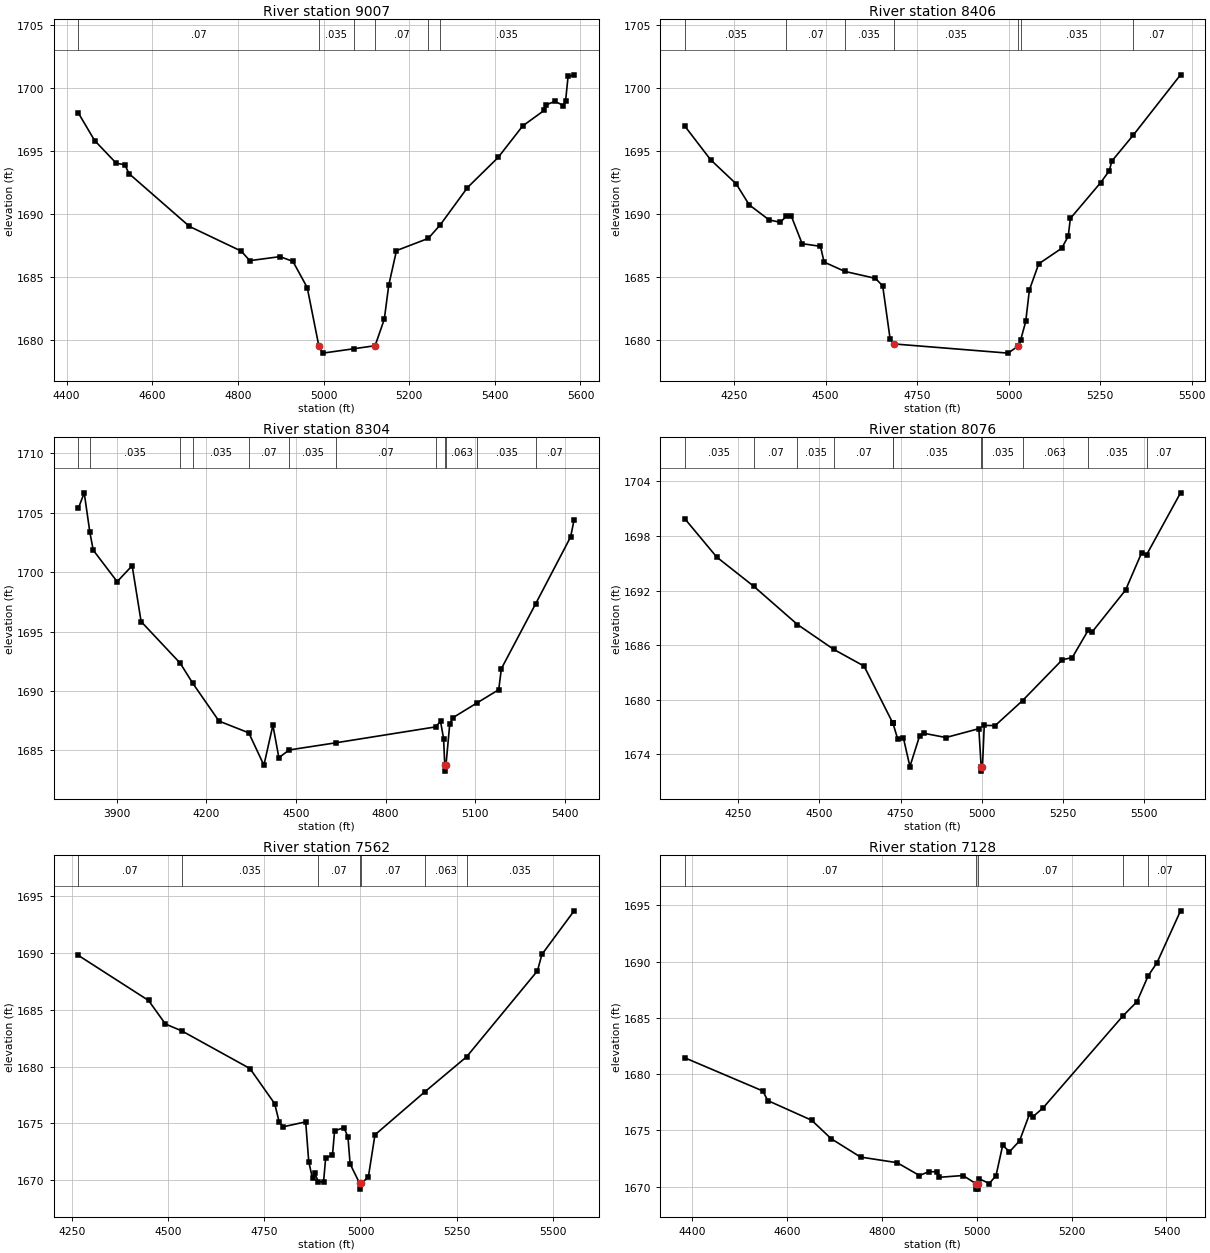
Type RM Length L Ch R = 1 ,9007    ,601,601,601
BEGIN DESCRIPTION:
Elm 02 46 18.0
END DESCRIPTION:
XS GIS Cut Line= 3
      1586380.83       6881655.8      1586315.44      6881086.94
      1586195.72      6880514.22
#Sta/Elev= 30
  4427.4 1698.04  4465.4 1695.85  4515.8 1694.05  4535.9 1693.92    4546 1693.21
  4686.9 1689.02  4807.7 1687.06  4827.8  1686.3  4898.3 1686.62  4928.5 1686.24
  4961.9 1684.16  4988.9 1679.54  4998.3 1678.95  5071.2  1679.3  5120.4 1679.54
  5141.9 1681.65  5152.2 1684.34  5170.3  1687.1  5244.6 1688.07  5272.4 1689.14
  5336.1 1692.11  5407.6  1694.5  5465.1 1697.01  5515.1 1698.24  5520.2 1698.69
  5540.4 1698.96    5560 1698.63  5565.1 1698.97    5571 1700.94  5585.1 1701.07
#Mann= 6 ,-1 , 0
  4427.4     .07       0  4988.9    .035       0  5071.2    .035       0
  5120.4     .07       0  5244.6     .07       0  5272.4    .035       0
Bank Sta=4988.9,5120.4
XS Rating Curve= 0 ,0
Exp/Cntr=0.3,0.1

Type RM Length L Ch R = 1 ,8406    ,102,102,102
BEGIN DESCRIPTION:
Elm 02 46 17.0
END DESCRIPTION:
XS GIS Cut Line= 4
      1586592.51      6881658.45      1586626.98      6880845.77
      1586613.03      6880692.31      1586464.87      6880334.58
#Sta/Elev= 30
    4115 1696.98  4185.5 1694.31  4255.6 1692.39  4291.1 1690.73  4345.7 1689.53
  4375.7 1689.35  4392.9 1689.82  4405.7 1689.87  4435.7 1687.65  4485.8 1687.44
  4495.8 1686.19  4552.4 1685.45  4635.9  1684.9  4655.9  1684.3    4676 1680.12
    4686  1679.7  4998.3 1678.97  5026.6 1679.54  5033.2 1680.05  5046.7 1681.48
  5056.7 1683.98  5082.2 1686.05  5144.7 1687.28  5162.9 1688.24  5168.6 1689.65
  5251.1 1692.48    5275 1693.43    5282  1694.2  5340.9 1696.27  5469.7 1701.04
#Mann= 7 ,-1 , 0
    4115    .035       0  4392.9     .07       0  4552.4    .035       0
    4686    .035       0  5026.6     .07       0  5033.2    .035       0
  5340.9     .07       0
Bank Sta=4686,5026.6
XS Rating Curve= 0 ,0
Exp/Cntr=0.3,0.1

Type RM Length L Ch R = 1 ,8304    ,228,228,228
BEGIN DESCRIPTION:
Elm 02 46 16.0
END DESCRIPTION:
XS GIS Cut Line= 4
      1586652.33      6881927.67      1586705.67      6881114.77
      1586701.29      6880743.37      1586597.36       6880281.9
#Sta/Elev= 30
  3771.8 1705.36  3791.5 1706.67  3810.4 1703.35  3821.6 1701.85  3901.7  1699.2
  3951.9 1700.54  3981.9 1695.84  4112.7 1692.34    4155 1690.64  4242.5 1687.47
  4342.2 1686.48  4392.8 1683.76  4422.9 1687.12  4442.9 1684.39  4477.2 1685.04
  4635.3 1685.65  4967.2 1686.98  4983.9 1687.44  4994.1    1686    4998 1683.76
  4998.3 1683.26    5002 1683.76  5014.6 1687.19  5024.9 1687.75  5107.5 1689.02
  5178.6 1690.11  5187.5 1691.88  5302.7 1697.36  5419.2 1702.96  5430.9 1704.41
#Mann= 12 ,-1 , 0
  3771.8     .07       0  3810.4    .035       0  4112.7     .07       0
    4155    .035       0  4342.2     .07       0  4477.2    .035       0
  4635.3     .07       0  4967.2    .063       0    4998    .063       0
    5002    .063       0  5107.5    .035       0  5302.7     .07       0
Bank Sta=4998,5002
XS Rating Curve= 0 ,0
Exp/Cntr=0.3,0.1

Type RM Length L Ch R = 1 ,8076    ,514,514,514
BEGIN DESCRIPTION:
Elm 02 46 15.5
END DESCRIPTION:
XS GIS Cut Line= 4
       1586931.5      6881765.85       1586820.4      6880883.12
      1586834.53       6880835.9      1586704.02      6880262.96
#Sta/Elev= 30
  4085.3 1699.89  4183.9 1695.67  4297.3 1692.48  4432.3 1688.27  4544.4 1685.53
  4637.5  1683.7  4725.9 1677.45  4726.1 1677.44  4726.5 1677.42  4740.6 1675.74
  4758.4 1675.84  4778.6 1672.67  4808.8 1676.08    4821 1676.33  4889.4 1675.86
  4990.8 1676.83    4998 1672.67  4998.3 1672.17    5002 1672.67  5007.5 1677.19
  5041.1 1677.17  5125.3 1679.91  5247.8  1684.4  5278.5 1684.64  5327.4 1687.63
  5340.1 1687.47  5442.6 1692.05  5491.9 1696.13  5507.7 1695.95  5611.9 1702.73
#Mann= 12 ,-1 , 0
  4085.3    .035       0  4297.3     .07       0  4432.3    .035       0
  4544.4     .07       0  4725.9    .035       0  4726.1     .07       0
  4726.5    .035       0    4998    .035       0    5002    .035       0
  5125.3    .063       0  5327.4    .035       0  5507.7     .07       0
Bank Sta=4998,5002
XS Rating Curve= 0 ,0
Exp/Cntr=0.3,0.1

Type RM Length L Ch R = 1 ,7562    ,434,434,434
BEGIN DESCRIPTION:
Elm 02 46 15.0
END DESCRIPTION:
XS GIS Cut Line= 4
      1587429.81      6881414.68      1587151.19      6880790.53
      1587068.68      6880761.97      1586852.37      6880291.88
#Sta/Elev= 30
  4266.9 1689.78  4449.4 1685.81  4493.2 1683.74    4536 1683.13  4712.9 1679.82
  4777.1 1676.73  4788.9  1675.1  4799.9  1674.7  4857.7 1675.13  4865.6 1671.63
  4875.4 1670.15  4880.9 1670.62  4890.6 1669.87  4904.1 1669.84  4909.6 1671.95
  4927.3 1672.21  4932.8 1674.34    4957 1674.62  4967.5 1673.81  4973.1 1671.43
    4998 1669.71  4998.3 1669.21    5002 1669.71  5020.5 1670.27  5037.7 1673.99
  5167.9 1677.79  5275.7 1680.85    5460 1688.42  5471.4 1689.86  5555.2  1693.7
#Mann= 7 ,-1 , 0
  4266.9     .07       0    4536    .035       0  4890.6     .07       0
    4998     .07       0    5002     .07       0  5167.9    .063       0
  5275.7    .035       0
Bank Sta=4998,5002
XS Rating Curve= 0 ,0
Exp/Cntr=0.3,0.1

Type RM Length L Ch R = 1 ,7128    ,498,498,498
BEGIN DESCRIPTION:
Elm 02 46 14.0
END DESCRIPTION:
XS GIS Cut Line= 3
      1587455.01      6881038.03      1587310.68        6880440.
        1587005.        6880138.
#Sta/Elev= 30
  4384.8 1681.46  4549.4 1678.51  4559.7 1677.66  4652.3 1675.91  4693.4 1674.27
  4755.2 1672.64  4832.4 1672.14  4879.4    1671  4899.2 1671.34  4916.1 1671.33
  4921.3 1670.84  4971.2    1671    4998 1670.29  4998.3 1669.79  5001.8 1669.79
    5002 1670.29  5005.5 1670.71  5026.6 1670.29  5040.8 1670.99  5054.9 1673.69
  5069.1 1673.11  5090.3 1674.07  5111.5 1676.47  5118.6 1676.22  5139.8    1677
  5307.8 1685.16  5337.8 1686.44  5361.3 1688.73  5380.2 1689.92  5429.7 1694.52
#Mann= 5 ,-1 , 0
  4384.8     .07       0    4998     .07       0    5002     .07       0
  5307.8    .035       0  5361.3     .07       0
Bank Sta=4998,5002
XS Rating Curve= 0 ,0
Exp/Cntr=0.3,0.1

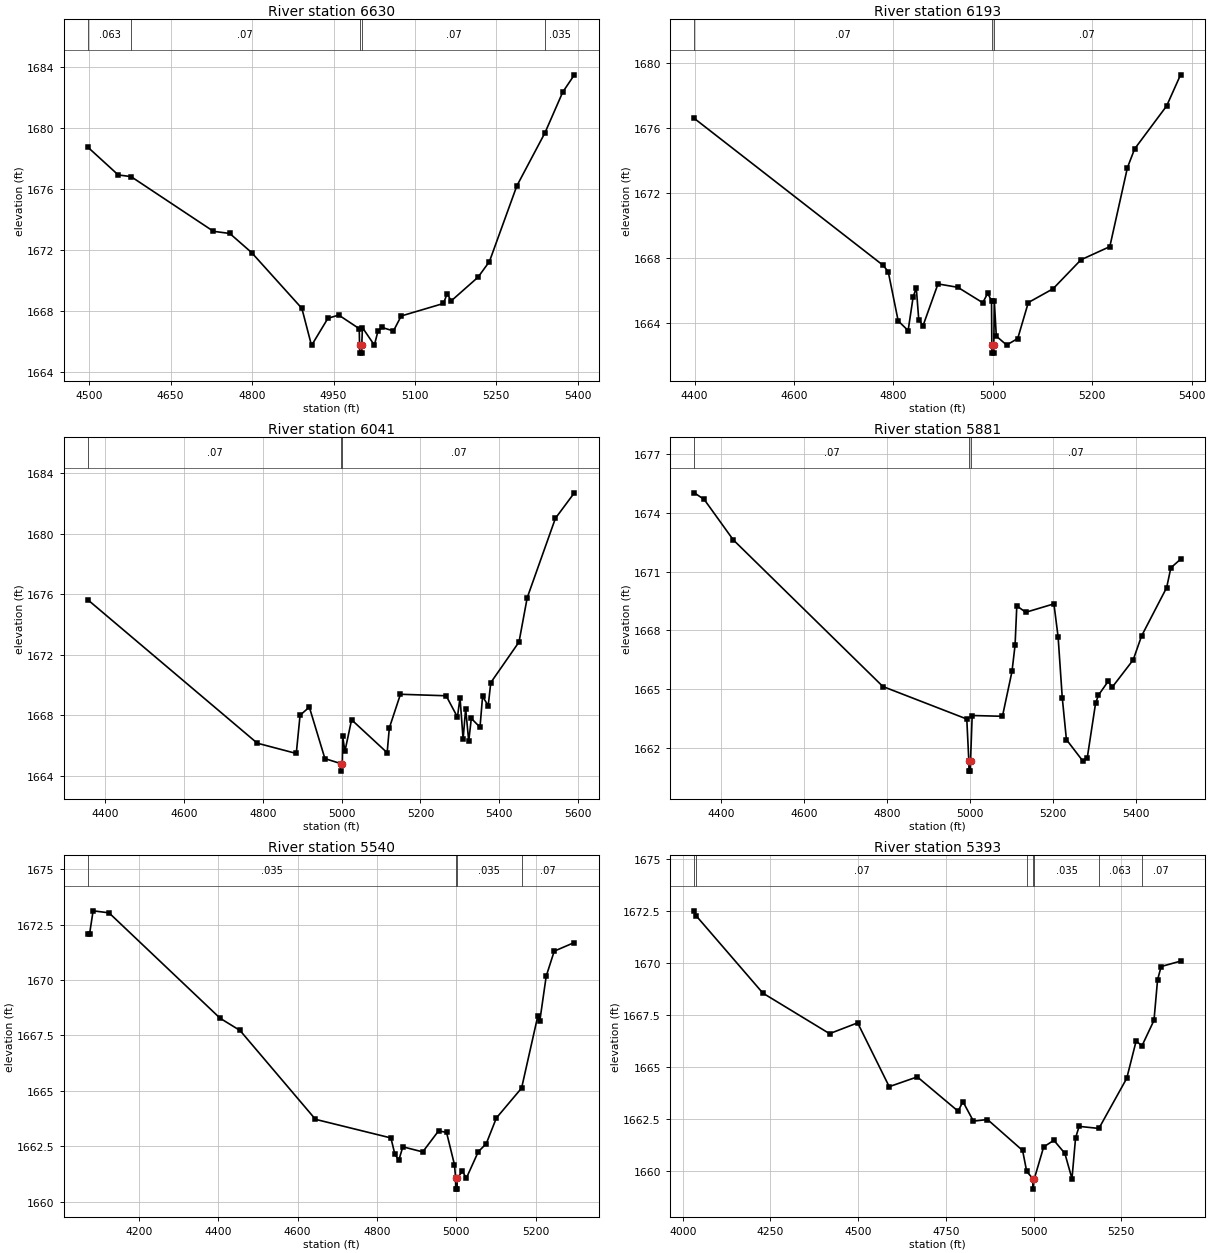
Type RM Length L Ch R = 1 ,6630    ,437,437,437
BEGIN DESCRIPTION:
Elm 02 46 13.0
END DESCRIPTION:
XS GIS Cut Line= 3
        1587805.      6880887.99      1587760.05      6880387.91
        1587505.        6880088.
#Sta/Elev= 30
  4497.9 1678.71  4553.4 1676.91    4577  1676.8  4728.8 1673.22  4758.9 1673.08
  4799.1 1671.83  4891.7 1668.18  4909.5 1665.75  4939.7 1667.53  4959.7 1667.74
  4997.4 1666.85    4998 1665.75  4998.3 1665.25  5001.8 1665.25    5002 1665.75
  5003.3 1666.92  5025.3 1665.77  5031.8 1666.68  5039.3 1666.93  5060.4  1666.7
  5074.7 1667.68  5152.6  1668.5  5159.2 1669.13  5166.9 1668.67  5216.3 1670.22
  5237.2 1671.24  5287.7 1676.19  5339.6 1679.67  5372.3 1682.33  5393.7 1683.46
#Mann= 5 ,-1 , 0
  4497.9    .063       0    4577     .07       0    4998     .07       0
    5002     .07       0  5339.6    .035       0
Bank Sta=4998,5002
XS Rating Curve= 0 ,0
Exp/Cntr=0.3,0.1

Type RM Length L Ch R = 1 ,6193    ,152,152,152
BEGIN DESCRIPTION:
Elm 02 46 12.0
END DESCRIPTION:
XS GIS Cut Line= 3
        1587955.        6880788.      1587934.89      6880187.74
      1587705.03      6879888.04
#Sta/Elev= 30
  4399.4  1676.6  4779.6 1667.53  4789.6 1667.14  4809.6 1664.11  4829.6 1663.51
  4839.6 1665.56    4846 1666.16    4851 1664.18  4859.7 1663.82  4889.7 1666.39
  4929.7 1666.18  4979.7 1665.23  4989.7 1665.81  4997.4 1665.35    4998 1662.62
  4998.3 1662.12  5001.8 1662.12    5002 1662.62    5003 1665.35    5007 1663.17
  5027.8 1662.62  5050.1 1663.02  5071.4 1665.24  5121.2 1666.09  5177.4 1667.88
  5235.4 1668.69  5270.8 1673.56  5285.3 1674.72  5349.7 1677.37  5377.7 1679.29
#Mann= 3 ,-1 , 0
  4399.4     .07       0    4998     .07       0    5002     .07       0
Bank Sta=4998,5002
XS Rating Curve= 0 ,0
Exp/Cntr=0.3,0.1

Type RM Length L Ch R = 1 ,6041    ,160,160,160
BEGIN DESCRIPTION:
Elm 02 46 11.0
END DESCRIPTION:
XS GIS Cut Line= 4
      1588076.43      6880784.11      1588028.86      6880230.58
      1588149.15       6879983.3      1587890.34      6879674.72
#Sta/Elev= 30
  4357.2 1675.62  4786.3 1666.14  4885.2 1665.46  4894.8 1667.99  4918.3 1668.53
  4957.8 1665.12    4998 1664.79  4998.3 1664.29    5002 1664.79  5002.9 1666.59
  5008.5  1665.6  5025.5 1667.69  5115.7 1665.51  5121.2 1667.15  5149.4 1669.38
  5265.3 1669.28    5294 1667.87  5300.5 1669.16  5308.3  1666.4  5314.8 1668.43
  5322.6 1666.26  5329.1 1667.78  5351.2  1667.2  5357.7 1669.24    5372 1668.62
  5378.5 1670.15  5450.1 1672.84  5470.9 1675.77  5542.4 1681.03  5590.5 1682.72
#Mann= 3 ,-1 , 0
  4357.2     .07       0    4998     .07       0    5002     .07       0
Bank Sta=4998,5002
XS Rating Curve= 0 ,0
Exp/Cntr=0.3,0.1

Type RM Length L Ch R = 1 ,5881    ,341,341,341
BEGIN DESCRIPTION:
Elm 02 46 10.8
END DESCRIPTION:
XS GIS Cut Line= 5
      1588299.45      6880791.84      1588285.81      6880379.92
      1588158.56      6880035.14      1588175.55      6879839.01
       1588150.2      6879644.78
#Sta/Elev= 30
    4336 1675.02  4359.9 1674.68  4429.9 1672.62  4790.7 1665.13    4993 1663.47
    4998 1661.31  4998.3 1660.81  5001.8 1660.81    5002 1661.31    5006 1663.65
    5079 1663.61    5102  1665.9  5109.4 1667.24  5113.6 1669.25  5135.1 1668.92
  5203.1 1669.35  5213.2 1667.66  5223.2 1664.56  5233.2 1662.42  5273.4 1661.31
  5283.4 1661.48  5303.5 1664.27  5310.5 1664.69  5333.7 1665.39  5343.8  1665.1
  5394.2 1666.49  5414.4 1667.71  5474.9 1670.18    5485 1671.19  5508.4 1671.63
#Mann= 3 ,-1 , 0
    4336     .07       0    4998     .07       0    5002     .07       0
Bank Sta=4998,5002
XS Rating Curve= 0 ,0
Exp/Cntr=0.3,0.1

Type RM Length L Ch R = 1 ,5540    ,147,147,147
BEGIN DESCRIPTION:
Elm 02 46 10.4
END DESCRIPTION:
XS GIS Cut Line= 3
      1588369.31      6880820.56      1588353.94      6879791.89
      1588328.59      6879597.72
#Sta/Elev= 30
  4072.5 1672.09  4076.3 1672.09  4085.1 1673.12  4125.1 1673.03  4405.1 1668.27
  4455.1 1667.72  4645.1 1663.71  4835.1 1662.87  4845.1 1662.13  4855.1 1661.87
  4865.1 1662.47  4915.2 1662.24  4955.2 1663.19  4975.2 1663.12  4995.2 1661.66
    4998 1661.06  4998.3 1660.56  5001.8 1660.56    5002 1661.06  5015.2 1661.36
  5025.2 1661.06  5055.2 1662.25  5075.2 1662.61  5100.7 1663.77  5164.2 1665.12
    5205 1668.37    5210 1668.14  5226.2 1670.17  5246.4  1671.3  5297.1 1671.69
#Mann= 4 ,-1 , 0
  4072.5    .035       0    4998    .035       0    5002    .035       0
  5164.2     .07       0
Bank Sta=4998,5002
XS Rating Curve= 0 ,0
Exp/Cntr=0.3,0.1

Type RM Length L Ch R = 1 ,5393    ,282,282,282
BEGIN DESCRIPTION:
Elm 02 46 10.2
END DESCRIPTION:
XS GIS Cut Line= 3
      1588481.25      6880953.45      1588465.88      6879924.78
      1588402.45      6879573.54
#Sta/Elev= 30
    4033 1672.53  4037.9  1672.3  4228.5 1668.57  4418.5 1666.62  4498.5 1667.14
  4588.5 1664.07  4668.5 1664.54  4784.8 1662.89  4798.5 1663.35  4828.5 1662.41
  4868.5 1662.49  4968.6    1661  4980.3 1659.99    4998 1659.64  4998.3 1659.14
    5002 1659.64  5028.6 1661.17  5057.7 1661.49    5089 1660.86  5109.3 1659.64
  5119.5  1661.6  5129.6 1662.16    5186 1662.06  5265.3 1664.47  5292.2 1666.27
  5308.6 1666.03    5343 1667.26  5353.2 1669.21  5363.4 1669.85  5418.7 1670.11
#Mann= 7 ,-1 , 0
    4033    .035       0  4037.9     .07       0  4980.3    .035       0
    4998    .035       0    5002    .035       0    5186    .063       0
  5308.6     .07       0
Bank Sta=4998,5002
XS Rating Curve= 0 ,0
Exp/Cntr=0.3,0.1

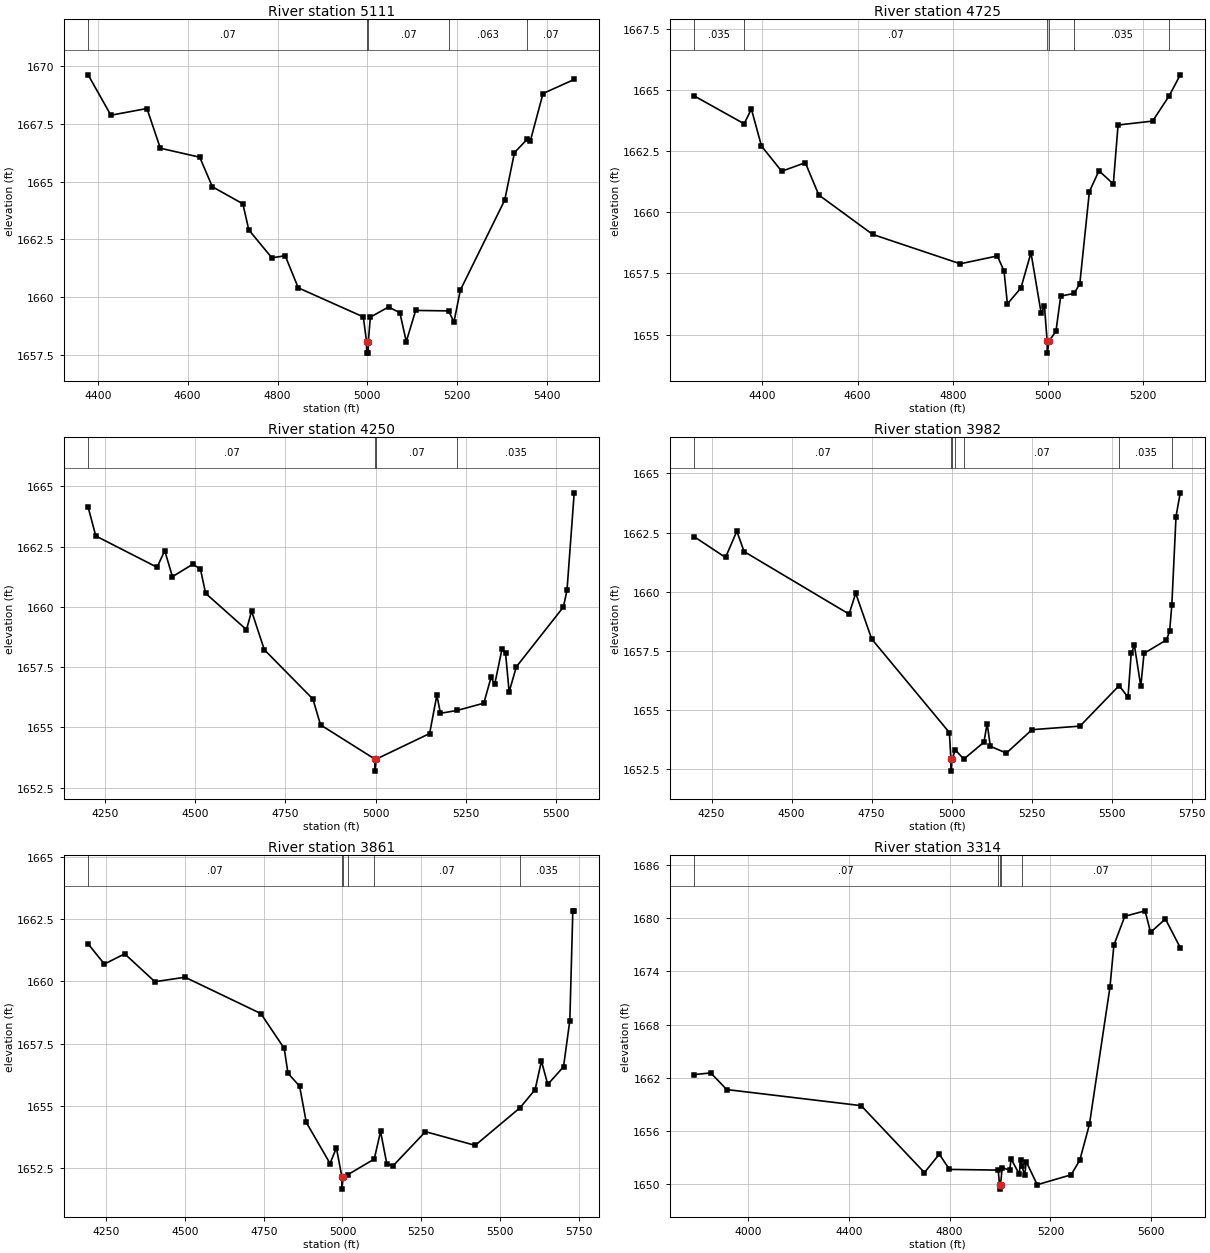
Type RM Length L Ch R = 1 ,5111    ,386,386,386
BEGIN DESCRIPTION:
Elm 02 46 10.0
END DESCRIPTION:
XS GIS Cut Line= 3
      1589035.55      6880456.79      1588697.62      6879877.33
      1588422.93      6879572.14
#Sta/Elev= 30
  4378.6 1669.63  4429.3 1667.88  4509.5 1668.17  4539.3 1666.45    4627 1666.06
    4655 1664.78  4722.9 1664.04  4736.1 1662.91  4787.4  1661.7  4817.1 1661.79
  4846.1  1660.4  4990.8 1659.14    4998 1658.07  4998.3 1657.57  5001.8 1657.57
    5002 1658.07  5006.5 1659.13    5047 1659.57  5072.2 1659.32  5086.4 1658.07
  5107.3 1659.42  5180.6  1659.4  5192.5 1658.92  5206.7  1660.3  5305.4  1664.2
  5327.1 1666.26    5356 1666.85  5362.2 1666.75  5390.6 1668.82    5460 1669.43
#Mann= 5 ,-1 , 0
  4378.6     .07       0    4998     .07       0    5002     .07       0
  5180.6    .063       0    5356     .07       0
Bank Sta=4998,5002
XS Rating Curve= 0 ,0
Exp/Cntr=0.3,0.1

Type RM Length L Ch R = 1 ,4725    ,475,475,475
BEGIN DESCRIPTION:
Elm 02 46 9.0
END DESCRIPTION:
XS GIS Cut Line= 3
      1589355.01      6880138.01      1588831.42      6879610.86
      1588554.96        6879588.
#Sta/Elev= 30
    4257 1664.75    4362 1663.61  4377.2 1664.21  4398.4  1662.7  4440.8 1661.67
  4490.4 1662.02  4518.7  1660.7  4631.8 1659.09  4815.6 1657.89  4893.4 1658.21
  4907.5  1657.6  4914.6 1656.25  4942.9  1656.9  4964.1 1658.34  4985.4 1655.88
  4992.4 1656.15    4998 1654.74  4998.3 1654.24    5002 1654.74  5016.5 1655.13
  5026.5 1656.57  5054.8 1656.68  5066.6 1657.08  5086.7 1660.84  5106.8 1661.69
  5136.9 1661.15  5146.9 1663.56  5219.4 1663.72  5254.5 1664.76  5277.4 1665.61
#Mann= 6 ,-1 , 0
    4257    .035       0    4362     .07       0    4998     .07       0
    5002     .07       0  5054.8    .035       0  5254.5     .07       0
Bank Sta=4998,5002
XS Rating Curve= 0 ,0
Exp/Cntr=0.3,0.1

Type RM Length L Ch R = 1 ,4250    ,268,268,268
BEGIN DESCRIPTION:
Elm 02 46 8.0
END DESCRIPTION:
XS GIS Cut Line= 3
      1589605.03      6879888.03      1589054.51      6879312.96
      1588504.98        6879338.
#Sta/Elev= 30
  4203.9 1664.14  4225.2 1662.94    4395 1661.64  4416.1 1662.33  4437.5 1661.25
  4494.1 1661.77  4515.1 1661.56  4529.3 1660.56  4642.5 1659.05  4656.7 1659.82
  4691.9 1658.22  4826.5 1656.17  4847.6  1655.1    4998 1653.68  4998.3 1653.18
    5002 1653.68  5149.7 1654.74  5169.7 1656.33  5179.7 1655.58  5226.3  1655.7
  5299.8    1656  5319.8 1657.07  5329.9 1656.78  5349.9 1658.23  5359.9 1658.09
  5369.9 1656.47  5389.9 1657.51  5520.1 1659.99  5530.1 1660.68  5550.1 1664.73
#Mann= 4 ,-1 , 0
  4203.9     .07       0    4998     .07       0    5002     .07       0
  5226.3    .035       0
Bank Sta=4998,5002
XS Rating Curve= 0 ,0
Exp/Cntr=0.3,0.1

Type RM Length L Ch R = 1 ,3982    ,121,121,121
BEGIN DESCRIPTION:
Elm 02 46 7.2
END DESCRIPTION:
XS GIS Cut Line= 3
       1589738.2      6879782.93      1589232.53      6879127.39
      1588541.78      6879135.49
#Sta/Elev= 30
  4195.7 1662.33  4293.8 1661.45  4329.1 1662.56  4351.8  1661.7  4679.7 1659.06
  4700.5 1659.94  4750.4 1658.01  4993.1 1654.06    4998 1652.93  4998.3 1652.43
    5002 1652.93  5011.3 1653.33  5038.4 1652.94  5101.1 1653.65  5111.1 1654.44
  5121.1 1653.48  5171.1 1653.19  5251.2 1654.18  5401.2 1654.33  5523.5 1656.04
  5551.2 1655.55  5561.2  1657.4  5571.2 1657.74  5591.2 1656.01  5601.2  1657.4
  5671.2 1657.97  5681.2 1658.33  5688.1 1659.44  5701.2 1663.18  5714.4 1664.18
#Mann= 7 ,-1 , 0
  4195.7     .07       0    4998     .07       0    5002     .07       0
  5011.3    .035       0  5038.4     .07       0  5523.5    .035       0
  5688.1     .07       0
Bank Sta=4998,5002
XS Rating Curve= 0 ,0
Exp/Cntr=0.3,0.1

Type RM Length L Ch R = 1 ,3861    ,547,547,547
BEGIN DESCRIPTION:
Elm 02 46 7.0
END DESCRIPTION:
XS GIS Cut Line= 3
      1589767.51      6879655.34      1589414.26      6879052.55
      1588571.12      6879007.89
#Sta/Elev= 30
  4192.5 1661.51  4244.2  1660.7  4308.7 1661.11  4404.5 1659.99  4500.3 1660.17
  4740.7 1658.71    4815 1657.31  4826.9 1656.31  4863.8 1655.79  4885.2 1654.33
  4960.5 1652.68  4980.6 1653.31    4998 1652.15  4998.3 1651.65    5002 1652.15
  5016.9 1652.23  5100.9 1652.86  5120.8 1653.97  5140.8 1652.66  5160.8 1652.59
  5263.3 1653.96  5421.2 1653.41  5563.4 1654.92  5611.4 1655.65  5631.5  1656.8
  5651.5 1655.86  5701.6 1656.57  5721.6 1658.43  5731.1 1662.84  5735.5 1662.84
#Mann= 6 ,-1 , 0
  4192.5     .07       0    4998     .07       0    5002     .07       0
  5016.9    .035       0  5100.9     .07       0  5563.4    .035       0
Bank Sta=4998,5002
XS Rating Curve= 0 ,0
Exp/Cntr=0.3,0.1

Type RM Length L Ch R = 1 ,3314    ,442,442,442
BEGIN DESCRIPTION:
Elm 02 46 6.0
END DESCRIPTION:
XS GIS Cut Line= 4
      1589854.99      6879737.97      1589348.93      6878635.58
       1589151.1      6878272.59      1589001.04      6878011.43
#Sta/Elev= 30
    3787 1662.34    3853 1662.53  3916.2 1660.65  4449.4 1658.83  4700.2 1651.26
  4759.2 1653.34  4799.3 1651.62  4992.8 1651.54    4998 1649.89  4998.3 1649.39
    5002 1649.89  5008.6 1651.82  5038.3 1651.54    5044 1652.81  5076.3 1651.08
    5082 1652.74  5086.9 1651.97  5098.1 1650.94  5103.8  1652.5  5147.5 1649.89
    5282 1651.01  5316.5 1652.68  5354.5 1656.71  5435.8 1672.21  5451.6    1677
  5494.8 1680.24  5575.3 1680.86  5596.9 1678.43  5655.8 1679.94  5714.6  1676.7
#Mann= 5 ,-1 , 0
    3787     .07       0  4992.8    .035       0    4998    .035       0
    5002    .035       0  5086.9     .07       0
Bank Sta=4998,5002
XS Rating Curve= 0 ,0
Exp/Cntr=0.3,0.1

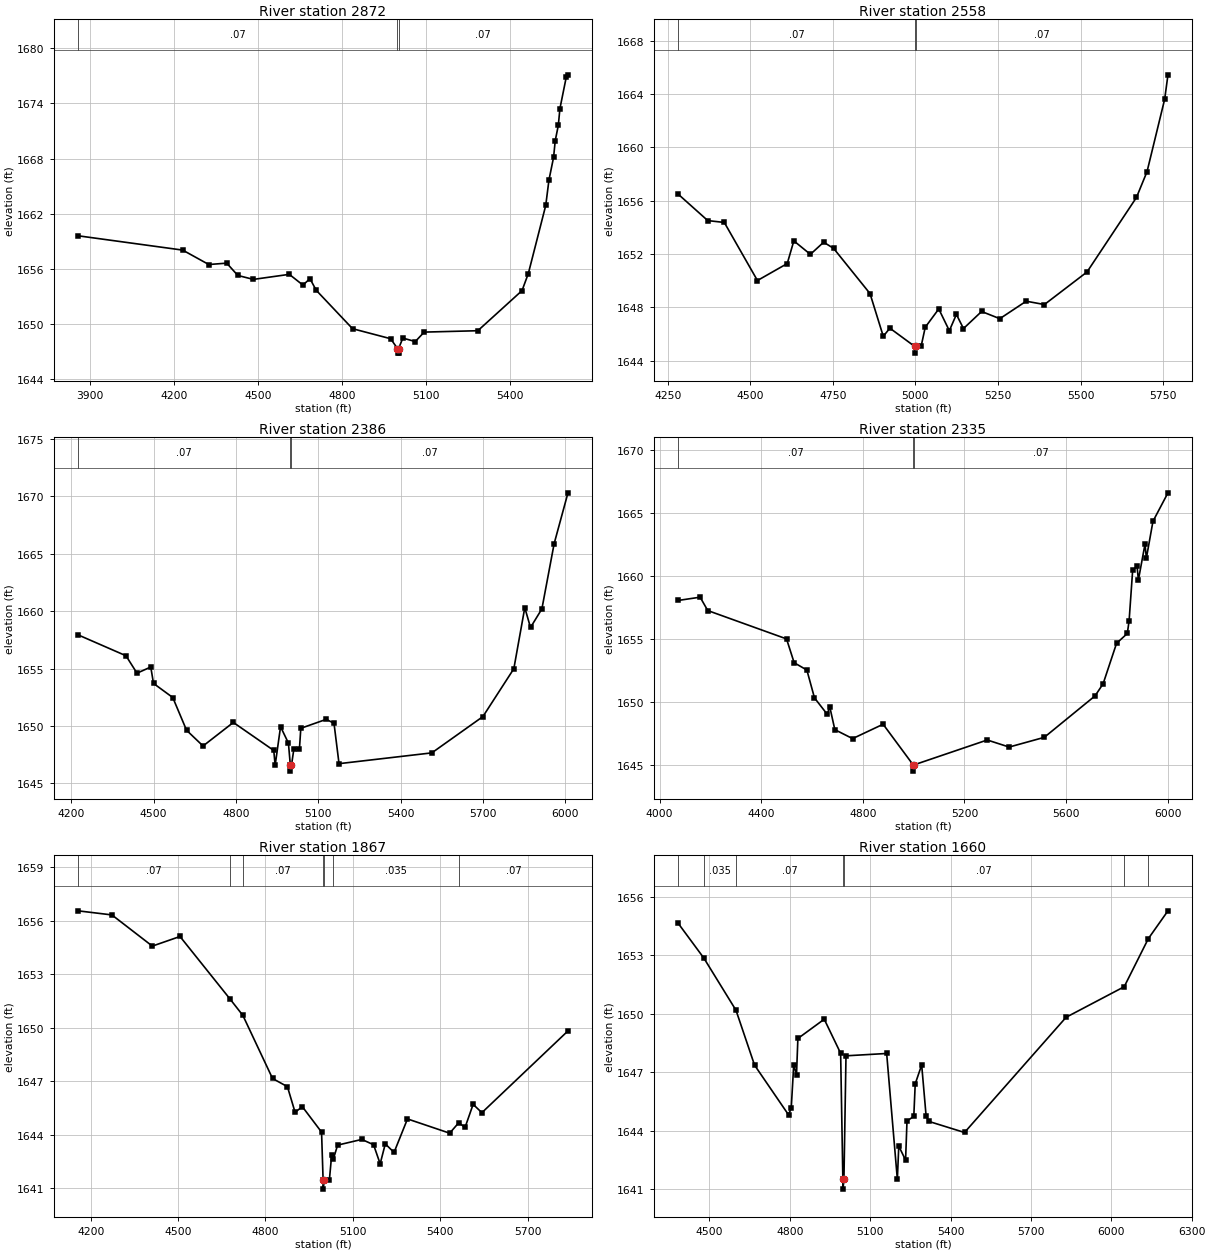
Type RM Length L Ch R = 1 ,2872    ,314,314,314
BEGIN DESCRIPTION:
Elm 02 46 5.0
END DESCRIPTION:
XS GIS Cut Line= 3
      1590098.64      6879566.49      1589702.55      6878493.47
       1589437.5      6877946.95
#Sta/Elev= 30
  3856.2 1659.59  4230.3 1658.03  4323.6 1656.46  4387.6 1656.61  4427.4 1655.27
  4482.9 1654.84  4611.4 1655.39  4660.1 1654.22  4685.2 1654.92  4707.4 1653.66
  4837.4 1649.47  4973.5 1648.38    4998 1647.31  4998.3 1646.81  5001.8 1646.81
    5002 1647.31  5017.2 1648.45  5061.6 1648.07  5093.5  1649.1  5285.2 1649.25
  5443.2 1653.62  5465.7 1655.48  5527.9 1662.89  5539.5 1665.68    5556 1668.14
  5561.8 1669.94  5572.9 1671.62  5578.6 1673.44  5601.2 1676.86  5607.4 1677.12
#Mann= 3 ,-1 , 0
  3856.2     .07       0    4998     .07       0    5002     .07       0
Bank Sta=4998,5002
XS Rating Curve= 0 ,0
Exp/Cntr=0.3,0.1

Type RM Length L Ch R = 1 ,2558    ,172,172,172
BEGIN DESCRIPTION:
Elm 02 46 4.6
END DESCRIPTION:
XS GIS Cut Line= 3
      1590053.05      6879117.82      1590007.88      6878453.46
      1589719.75      6877688.73
#Sta/Elev= 30
  4281.4  1656.5  4371.4 1654.51  4421.5 1654.37  4521.8 1650.02    4612 1651.29
    4632 1652.99  4682.1 1651.98  4722.2 1652.89  4752.3 1652.43  4862.6 1649.04
  4902.7 1645.84  4922.7 1646.45    4998 1645.08  4998.3 1644.58    5002 1645.08
  5017.2 1645.08  5029.8 1646.52  5070.7 1647.89  5102.7 1646.26  5124.1 1647.48
  5145.5 1646.42  5200.4  1647.7  5255.5 1647.16  5335.4 1648.47  5390.5 1648.22
  5519.5 1650.66  5669.1 1656.24  5701.2 1658.18  5754.6 1663.61  5764.5 1665.43
#Mann= 3 ,-1 , 0
  4281.4     .07       0    4998     .07       0    5002     .07       0
Bank Sta=4998,5002
XS Rating Curve= 0 ,0
Exp/Cntr=0.3,0.1

Type RM Length L Ch R = 1 ,2386    ,51,51,51
BEGIN DESCRIPTION:
Elm 02 46 4.1
END DESCRIPTION:
XS GIS Cut Line= 5
       1590076.5      6879242.16      1590131.71      6878506.55
      1590143.91      6878398.81      1590077.09      6878351.36
      1589845.81      6877526.53
#Sta/Elev= 30
  4224.6 1657.94  4399.2 1656.12  4439.4  1654.6  4489.5 1655.14  4499.5 1653.71
  4569.7 1652.48  4619.9 1649.63    4680 1648.26  4790.3 1650.31  4937.6 1647.87
  4942.6 1646.57  4962.3 1649.94    4991 1648.51    4998 1646.57  4998.3 1646.07
    5002 1646.57  5011.1 1648.04  5031.1 1648.01  5036.1  1649.8  5128.6 1650.58
    5157 1650.24  5175.3 1646.72  5513.4 1647.66  5699.4 1650.82  5812.1 1654.99
    5852 1660.31  5872.8 1658.58  5914.3  1660.2  5958.9 1665.88  6009.3 1670.31
#Mann= 3 ,-1 , 0
  4224.6     .07       0    4998     .07       0    5002     .07       0
Bank Sta=4998,5002
XS Rating Curve= 0 ,0
Exp/Cntr=0.3,0.1

Type RM Length L Ch R = 1 ,2335    ,468,468,468
BEGIN DESCRIPTION:
Elm 02 46 4.0
END DESCRIPTION:
XS GIS Cut Line= 3
       1590207.6      6879414.92      1590179.23      6878408.78
      1589881.15      6877536.55
#Sta/Elev= 30
  4072.7 1658.06  4159.7 1658.32  4189.7 1657.26  4499.8 1655.01  4529.8 1653.12
  4579.8 1652.54  4609.8 1650.33  4659.9 1649.03  4669.9 1649.62  4689.9 1647.81
  4759.9  1647.1  4879.9 1648.24    4998 1645.02  4998.3 1644.52    5002 1645.02
  5289.7 1646.99    5376 1646.43  5514.2  1647.2  5714.1 1650.49  5745.8 1651.45
  5798.7 1654.66    5841 1655.44  5848.1 1656.45  5862.1 1660.47  5879.4 1660.76
  5884.7 1659.69  5910.7 1662.53    5916 1661.41    5942 1664.34    6001  1666.6
#Mann= 3 ,-1 , 0
  4072.7     .07       0    4998     .07       0    5002     .07       0
Bank Sta=4998,5002
XS Rating Curve= 0 ,0
Exp/Cntr=0.3,0.1

Type RM Length L Ch R = 1 ,1867    ,207,207,207
BEGIN DESCRIPTION:
Elm 02 46 3.0
END DESCRIPTION:
XS GIS Cut Line= 4
      1590467.76      6879411.89      1590630.29      6878632.25
      1590604.54      6878538.39      1590523.34      6877754.01
#Sta/Elev= 30
  4156.5 1656.56  4272.8 1656.33  4411.6 1654.58  4506.6 1655.12  4677.9 1651.62
  4722.5 1650.69  4824.4 1647.15  4875.5 1646.69  4901.8 1645.25  4926.6 1645.57
  4992.7 1644.14    4998 1641.44  4998.3 1640.94    5002 1641.44  5019.5 1641.44
  5027.2 1642.83  5033.6 1642.65  5047.8 1643.41    5131 1643.73  5171.3 1643.43
  5193.9 1642.36  5211.5 1643.48  5241.6    1643  5287.7 1644.88  5432.6 1644.08
  5463.9 1644.67  5485.4  1644.4  5513.1  1645.7  5543.2 1645.23  5838.8 1649.82
#Mann= 7 ,-1 , 0
  4156.5     .07       0  4677.9    .035       0  4722.5     .07       0
    4998     .07       0    5002     .07       0  5033.6    .035       0
  5463.9     .07       0
Bank Sta=4998,5002
XS Rating Curve= 0 ,0
Exp/Cntr=0.3,0.1

Type RM Length L Ch R = 1 ,1660    ,201,201,201
BEGIN DESCRIPTION:
Elm 02 46 2.5
END DESCRIPTION:
XS GIS Cut Line= 6
      1590619.92      6879054.05      1590696.31      6878624.62
      1590810.46      6878602.51      1590805.65      6878379.21
      1590679.72      6878333.93      1590479.03      6877436.93
#Sta/Elev= 30
  4382.7 1654.66  4479.2 1652.86  4599.1 1650.18  4668.4 1647.36  4795.1 1644.81
  4805.3 1645.16  4814.6 1647.37    4825 1646.87  4830.1 1648.73  4928.5 1649.72
  4989.7 1647.97    4998 1641.49  4998.3 1640.99    5002 1641.49  5009.7 1647.84
  5161.5 1647.96  5201.4 1641.49  5206.7  1643.2  5232.1 1642.48  5237.4 1644.49
  5262.8 1644.73  5268.1  1646.4  5292.2 1647.37  5308.6 1644.77  5318.9 1644.47
  5452.1  1643.9  5831.3 1649.82  6048.2 1651.39  6138.2 1653.86  6211.5 1655.29
#Mann= 7 ,-1 , 0
  4382.7     .07       0  4479.2    .035       0  4599.1     .07       0
    4998     .07       0    5002     .07       0  6048.2     .16       0
  6138.2     .07       0
Bank Sta=4998,5002
XS Rating Curve= 0 ,0
Exp/Cntr=0.3,0.1