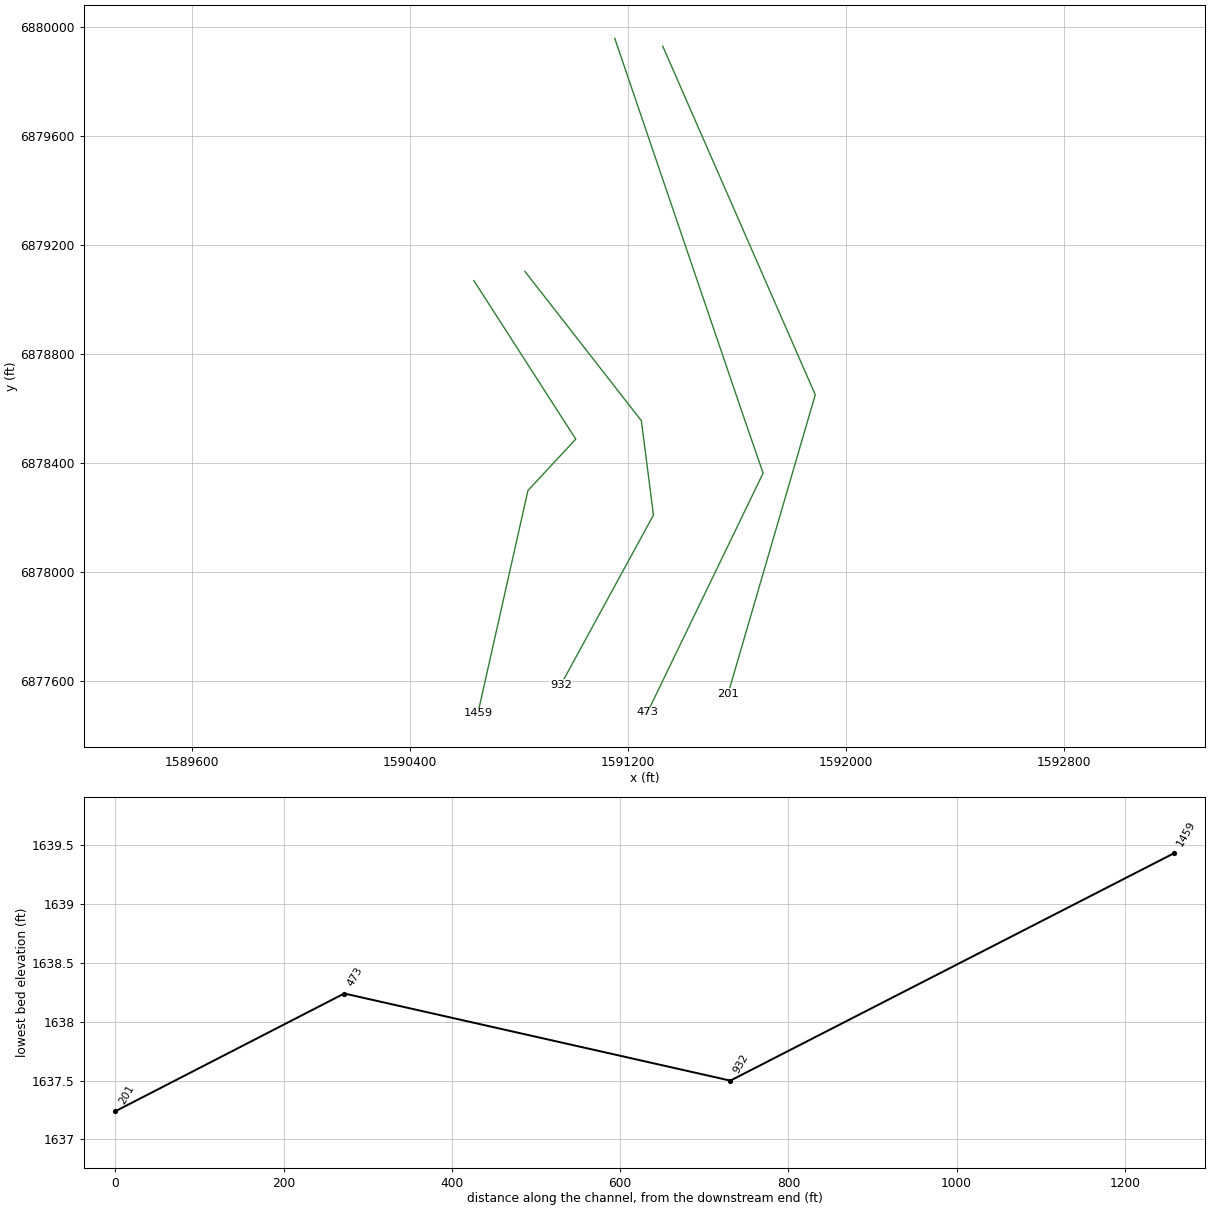
HEC-RAS study Elm 02 46.prj: Elm 02 46 Base Level Engineering

--- Elm 02 46.g01 (geometry) --- (continued)

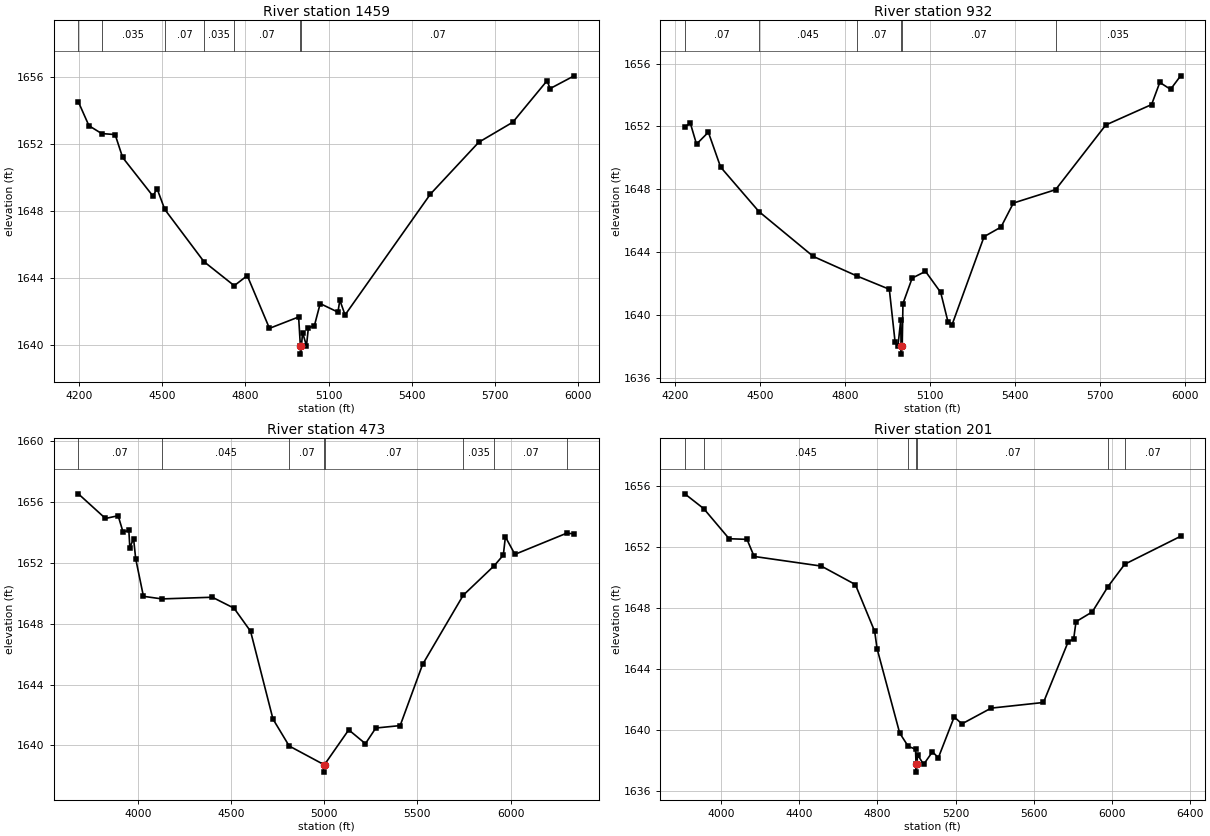
Type RM Length L Ch R = 1 ,1459    ,527,527,527
BEGIN DESCRIPTION:
Elm 02 46 2.0
END DESCRIPTION:
XS GIS Cut Line= 4
      1590635.38      6879070.09      1591009.34      6878488.51
      1590833.88       6878299.9      1590650.22      6877482.42
#Sta/Elev= 30
  4197.8 1654.51    4236 1653.08  4281.9 1652.61  4330.4 1652.55  4357.5 1651.18
  4466.5 1648.88  4481.7 1649.31  4509.2 1648.08  4650.3 1644.96  4759.7 1643.52
  4806.6 1644.12  4886.6 1640.97  4991.7 1641.65    4998 1639.93  4998.3 1639.43
    5002 1639.93  5005.9 1640.72    5020 1639.93  5026.9 1641.01  5048.4 1641.12
  5069.4 1642.45  5133.4 1641.94  5140.2 1642.66    5159 1641.77  5466.5 1648.99
  5640.8 1652.09  5763.7 1653.29  5886.7 1655.76  5898.3  1655.3  5984.7 1656.06
#Mann= 7 ,-1 , 0
  4197.8     .07       0  4281.9    .035       0  4509.2     .07       0
  4650.3    .035       0  4759.7     .07       0    4998     .07       0
    5002     .07       0
Bank Sta=4998,5002
XS Rating Curve= 0 ,0
Exp/Cntr=0.3,0.1

Type RM Length L Ch R = 1 ,932     ,459,459,459
BEGIN DESCRIPTION:
Elm 02 46 1.0
END DESCRIPTION:
XS GIS Cut Line= 4
      1590822.91       6879103.6      1591249.94      6878555.83
      1591294.31      6878209.89      1590954.98      6877587.96
#Sta/Elev= 30
  4233.9 1651.98  4253.7 1652.19  4275.3 1650.87  4317.1 1651.63  4360.4 1649.41
  4495.7 1646.58  4687.9 1643.72  4842.7 1642.47  4956.5 1641.63  4976.7  1638.3
  4986.8    1638  4996.8 1639.66    4998    1638  4998.3  1637.5    5002    1638
  5004.7 1640.72  5037.2 1642.34  5084.3 1642.77    5138 1641.43    5164 1639.54
  5178.3 1639.38  5291.3 1644.98  5351.1 1645.59  5394.8 1647.12  5543.9 1647.97
  5721.3 1652.09  5883.1 1653.39  5912.1  1654.8  5950.1 1654.36  5985.7 1655.22
#Mann= 6 ,-1 , 0
  4233.9     .07       0  4495.7    .045       0  4842.7     .07       0
    4998     .07       0    5002     .07       0  5543.9    .035       0
Bank Sta=4998,5002
XS Rating Curve= 0 ,0
Exp/Cntr=0.3,0.1

Type RM Length L Ch R = 1 ,473     ,272,272,272
BEGIN DESCRIPTION:
Elm 02 46 0.5
END DESCRIPTION:
XS GIS Cut Line= 4
      1591152.35      6879958.64      1591620.07      6878585.14
      1591696.52      6878363.64      1591272.17       6877485.8
#Sta/Elev= 30
    3681 1656.54  3826.6 1654.92  3894.5  1655.1  3920.6 1654.04    3952 1654.13
  3957.3 1653.01  3977.5 1653.59  3988.6 1652.28  4030.3  1649.8  4129.9 1649.63
    4400 1649.74  4516.4 1649.02  4605.2  1647.5  4725.3 1641.73  4812.2 1639.96
  4997.8 1638.74  4998.1 1638.24  5002.2 1638.74  5131.8 1641.02  5221.3 1640.11
    5277 1641.14  5407.8  1641.3    5528 1645.32    5746 1649.87  5912.9 1651.82
  5961.2 1652.51  5972.3 1653.71  6023.5 1652.56  6300.9 1653.95  6341.3 1653.91
#Mann= 8 ,-1 , 0
    3681     .07       0  4129.9    .045       0  4812.2     .07       0
  4997.8     .07       0  5002.2     .07       0    5746    .035       0
  5912.9     .07       0  6300.9    .035       0
Bank Sta=4997.8,5002.2
XS Rating Curve= 0 ,0
Exp/Cntr=0.3,0.1

Type RM Length L Ch R = 1 ,201     ,0,0,0
BEGIN DESCRIPTION:
Elm 02 46 0.1
END DESCRIPTION:
XS GIS Cut Line= 3
      1591328.38      6879929.82      1591887.84      6878651.34
      1591567.73      6877553.69
#Sta/Elev= 30
  3813.6 1655.46  3910.6 1654.49  4040.7 1652.52  4132.1 1652.48  4168.6 1651.36
  4512.4 1650.73    4687 1649.52    4786 1646.45    4798 1645.33  4913.9  1639.8
  4957.5 1638.93    4995 1638.74  4997.8 1637.74  4998.1 1637.24  5002.2 1637.74
  5005.4 1638.39  5036.3 1637.74  5081.8 1638.57  5111.9 1638.18    5193 1640.85
  5232.7  1640.4  5382.3 1641.43  5650.1  1641.8  5776.6 1645.77  5804.9 1645.96
  5816.8 1647.09  5900.1 1647.73  5980.7 1649.39  6066.2 1650.85  6352.5 1652.68
#Mann= 7 ,-1 , 0
  3813.6     .07       0  3910.6    .045       0  4957.5     .07       0
  4997.8     .07       0  5002.2     .07       0  5980.7    .035       0
  6066.2     .07       0
Bank Sta=4997.8,5002.2
XS Rating Curve= 0 ,0
Exp/Cntr=0.3,0.1

Chan Stop Cuts=-1
Use User Specified Reach Order=0
Composite Channel Slope=5