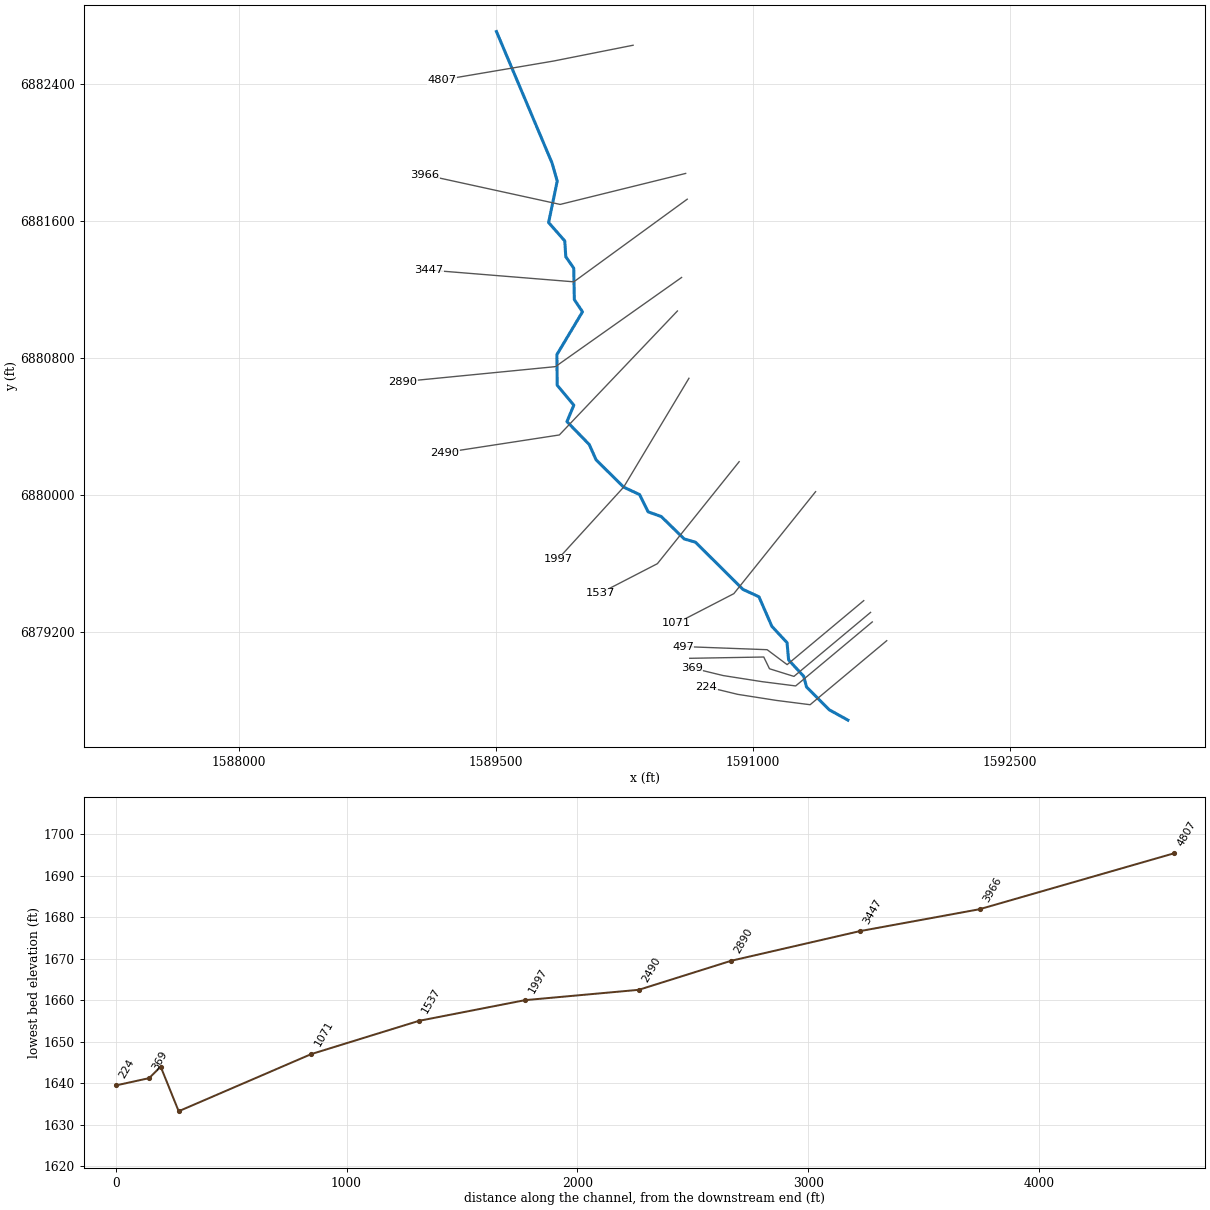
--- Elm 02 47.prj (project) ---

Proj Title=Elm 02 47 Base Level Engineering
Current Plan=p01
Default Exp/Contr=0.3,0.1
English Units
Geom File=g01
Flow File=f01
Plan File=p01
Y Axis Title=Elevation
X Axis Title(PF)=Main Channel Distance
X Axis Title(XS)=Station
BEGIN DESCRIPTION:
Elm 02 47
END DESCRIPTION:
DSS Export Rating Curves= 0
DSS Export Rating Curve Sorted= 0
DSS Export Volume Flow Curves= 0
DXF OffsetX= 0
DXF OffsetY= 0
DXF ScaleX= 1
DXF ScaleY= 10

--- Elm 02 47.p01 (plan) ---

Plan Title=Multiple Run
Program Version=4.10
Short Identifier=Multiple
Geom File=g01
Flow File=f01
Subcritical Flow
K Sum by GR= 0
Std Step Tol= 0.01
Critical Tol= 0.01
Num of Std Step Trials= 20
Max Error Tol= 0.3
Flow Tol Ratio= 0.001
Split Flow NTrial= 30
Split Flow Tol= 0.02
Split Flow Ratio= 0.02
Log Output Level= 0
Friction Slope Method= 1
Unsteady Friction Slope Method= 2
Unsteady Bridges Friction Slope Method= 1
Parabolic Critical Depth
Global Vel Dist= 1 , 1 , 1
Global Log Level= 0
CheckData=True
Encroach Param=-1 ,0,0, 0
BEGIN DESCRIPTION:
Multiple Run
END DESCRIPTION:
Computation Interval=1HOUR
Output Interval=1HOUR
Run HTab= 0
Run UNet= 0
Run PostProcess= 0
Run WQNet= 0
UNET Theta= 1
UNET Theta Warmup= 1
UNET ZTol= 0.02
UNET ZSATol= 0.05
UNET MxIter= 20
UNET MaxInSteps= 0
UNET DtIC= 0
UNET DtMin= 0
UNET MaxCRTS= 20
UNET WFStab= 2
UNET SFStab= 1
UNET WFX= 1
UNET SFX= 1
UNET DSS MLevel= 4
UNET DZMax Abort= 100
UNET Convert EG Bridges= 0
UNET Use Existing IB Tables=-1
UNET Froude Reduction=False
UNET Froude Limit= 1
UNET Froude Power= 10
UNET Time Slicing=0,0, 5
UNET Junction Losses=0
Instantaneous Interval=1HOUR
Write IC File= 0
Write IC File at Sim End=0
Echo Input=False
Echo Parameters=False
Echo Output=False
Write Detailed= 0
WQ AD Non Conservative
WQ ULTIMATE=-1
WQ Max Comp Step=1HOUR
WQ Output Interval=15MIN
WQ Output Selected Increments= 0
WQ Output face flow=0
WQ Output face velocity=0
WQ Output face area=0
WQ Output face dispersion=0
WQ Output cell volume=0
WQ Output cell surface area=0
WQ Output cell continuity=0
WQ Output cumulative cell continuity=0
WQ Output face conc=0
WQ Output face dconc_dx=0
WQ Output face courant=0
WQ Output face peclet=0
WQ Output face adv mass=0
WQ Output face disp mass=0
WQ Output cell mass=0
WQ Output cell source sink temp=0
WQ Output cell source sink nsm=0
WQ Output MaxMinRange=-1
WQ Daily Max Min Mean=-1
WQ Daily Range=0
WQ Daily Time=0
WQ Create Restart=0
WQ Fixed Restart=0
WQ System Summary=0
WQ Use Fixed Temperature=0
Sorting and Armoring Iterations= 10
XS Update Threshold= 0.02
Hydraulics Update Threshold= 0.02
Energy Slope Method= 1
Volume Change Method= 0
XS Weighting Method= 0
Number of US Weighted Cross Sections= 1
Number of DS Weighted Cross Sections= 1
Upstream XS Weight=0.25
Main XS Weight=0.5
Downstream XS Weight=0.25
Number of DS XS's Weighted with US Boundary= 1
Upstream Boundary Weight= 1
Weight of XSs Associated with US Boundary= 0
Number of US XS's Weighted with DS Boundary= 1
Downstream Boundary Weight= 0.5
Weight of XSs Associated with DS Boundary= 0.5
Sediment Output Level= 4
Mass or Volume Output= 0
Output Increment Type= 1
Profile and TS Output Increment= 10
XS Output Flag= 0
XS Output Increment= 10
Disregard all LS=0
Disregard all Conn=0
Disregard all Breaches=0
Disregard all Pumps=0

--- Elm 02 47.f01 (steady flow) ---

Flow Title=Multiple
Program Version=4.10
Number of Profiles= 7
Profile Names=10-year,25-year,50-year,1pct_min,100-year,1pct_plu,500-year
River Rch & RM=Elm 02 47,Reach-1         ,4807
     215     296     361     220     439     876     657
River Rch & RM=Elm 02 47,Reach-1         ,3966
      65      83      97      57     113     225     154
Boundary for River Rch & Prof#=Elm 02 47,Reach-1         , 1
Up Type= 0
Dn Type= 3
Dn Slope=0.012
Boundary for River Rch & Prof#=Elm 02 47,Reach-1         , 2
Up Type= 0
Dn Type= 3
Dn Slope=0.012
Boundary for River Rch & Prof#=Elm 02 47,Reach-1         , 3
Up Type= 0
Dn Type= 3
Dn Slope=0.012
Boundary for River Rch & Prof#=Elm 02 47,Reach-1         , 4
Up Type= 0
Dn Type= 3
Dn Slope=0.012
Boundary for River Rch & Prof#=Elm 02 47,Reach-1         , 5
Up Type= 0
Dn Type= 3
Dn Slope=0.012
Boundary for River Rch & Prof#=Elm 02 47,Reach-1         , 6
Up Type= 0
Dn Type= 3
Dn Slope=0.012
Boundary for River Rch & Prof#=Elm 02 47,Reach-1         , 7
Up Type= 0
Dn Type= 3
Dn Slope=0.012
DSS Import GetInterval= 0
DSS Import GetPeak= 0
DSS Import FillOption= 0

--- Elm 02 47.g01 (geometry) ---

Geom Title=Existing Conditions
Program Version=4.10

River Reach=Elm 02 47       ,Reach-1
Reach XY= 30
      1589502.56      6882709.07      1589827.15      6881941.42
      1589857.37      6881835.86      1589807.02      6881593.84
      1589901.38       6881486.5      1589907.36      6881393.98
      1589953.78       6881327.5      1589957.29      6881143.93
      1590004.97      6881072.58       1589855.5      6880822.79
      1589857.07      6880643.86      1589954.35      6880527.36
      1589914.15      6880431.27      1590044.22      6880297.68
      1590084.62      6880207.84      1590245.34      6880048.79
       1590338.5      6880005.04      1590387.95       6879904.5
      1590464.66      6879877.21      1590598.95      6879746.16
      1590664.68      6879727.22       1590941.8      6879451.64
      1591035.38      6879408.47      1591110.85      6879235.71
      1591199.46      6879140.42      1591208.63       6879039.5
      1591296.82      6878944.04      1591313.16      6878881.95
      1591445.29       6878748.7        1591555.        6878688.

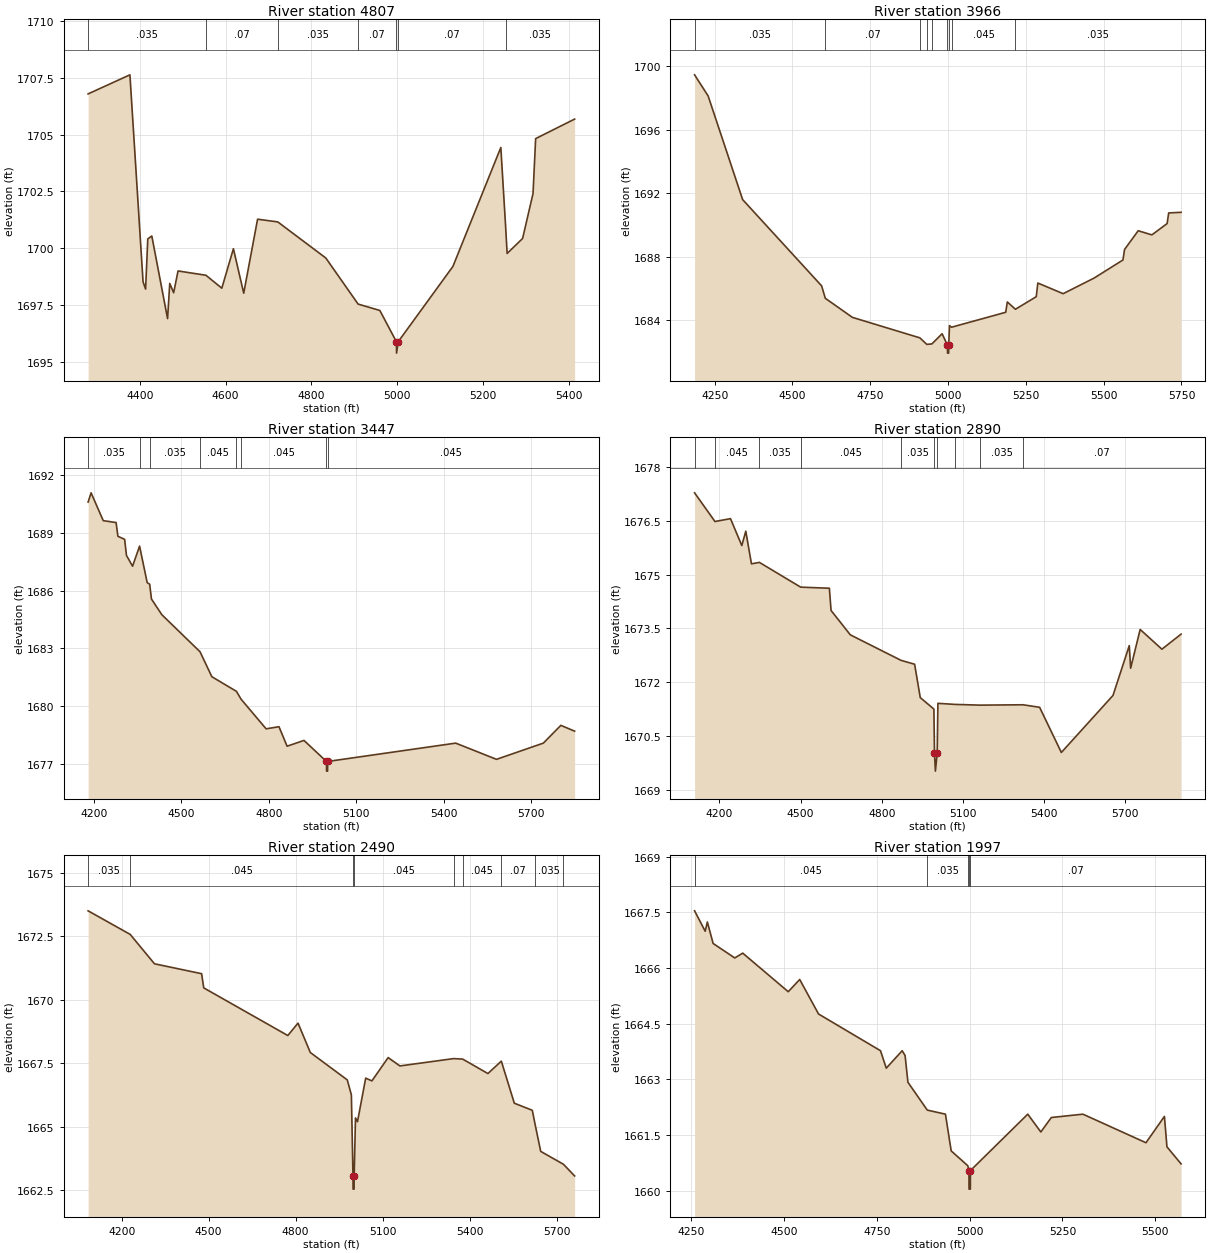
Type RM Length L Ch R = 1 ,4807    ,841,841,841
BEGIN DESCRIPTION:
Elm 02 47 7.0
END DESCRIPTION:
XS GIS Cut Line= 3
      1590300.53      6882629.26      1589834.43      6882536.67
       1589185.5      6882426.64
#Sta/Elev= 30
  4279.7 1706.79  4377.1 1707.63  4407.7 1698.51  4413.6 1698.19  4418.7  1700.4
  4428.1 1700.53  4464.8 1696.89  4469.9 1698.44    4479 1698.03  4489.2 1698.99
  4554.2  1698.8  4591.2 1698.23  4618.2 1699.97  4642.2 1698.01  4674.5 1701.27
  4721.6 1701.15  4833.5 1699.56  4908.7 1697.53  4959.3 1697.25    4998 1695.87
  4998.3 1695.37    5002 1695.87  5129.6 1699.19  5241.2 1704.43  5252.1 1701.03
  5255.9 1699.76  5291.9 1700.42  5316.2  1702.4  5322.3 1704.82  5413.1 1705.68
#Mann= 7 ,-1 , 0
  4279.7    .035       0  4554.2     .07       0  4721.6    .035       0
  4908.7     .07       0    4998     .07       0    5002     .07       0
  5252.1    .035       0
Bank Sta=4998,5002
XS Rating Curve= 0 ,0
Exp/Cntr=0.3,0.1

Type RM Length L Ch R = 1 ,3966    ,519,519,519
BEGIN DESCRIPTION:
Elm 02 47 6.0
END DESCRIPTION:
XS GIS Cut Line= 3
      1590607.35      6881880.64      1589874.46      6881699.67
      1589084.81      6881872.31
#Sta/Elev= 30
  4185.5 1699.44  4229.1 1698.11  4339.9 1691.59  4593.8 1686.16  4605.5 1685.38
  4692.6 1684.18  4909.4 1682.89  4931.7 1682.48  4948.1 1682.51  4980.8 1683.15
    4998 1682.43  4998.3 1681.93  5001.8 1681.93    5002 1682.43  5004.6 1683.66
  5011.1 1683.56  5185.2  1684.5  5190.4 1685.15  5216.4 1684.69  5283.3 1685.48
  5288.4 1686.34  5369.8 1685.67    5469 1686.65  5561.9 1687.79    5567 1688.45
  5610.9 1689.63  5654.8 1689.37  5703.8 1690.08  5708.9 1690.75  5748.7 1690.79
#Mann= 9 ,-1 , 0
  4185.5    .035       0  4605.5     .07       0  4909.4    .035       0
  4931.7    .045       0  4948.1    .035       0    4998    .035       0
    5002    .035       0  5011.1    .045       0  5216.4    .035       0
Bank Sta=4998,5002
XS Rating Curve= 0 ,0
Exp/Cntr=0.3,0.1

Type RM Length L Ch R = 1 ,3447    ,557,557,557
BEGIN DESCRIPTION:
Elm 02 47 5.0
END DESCRIPTION:
XS GIS Cut Line= 3
       1590616.6      6881730.19      1589954.22      6881247.67
        1589108.      6881316.38
#Sta/Elev= 30
  4180.5 1690.58  4190.7 1691.06  4232.4 1689.62  4276.5 1689.52  4282.6 1688.81
  4305.8 1688.65    4312 1687.82  4332.9 1687.26    4357  1688.3  4383.1 1686.41
  4391.6 1686.33  4397.8 1685.56  4433.3 1684.75  4564.4 1682.83  4604.8 1681.54
  4689.2 1680.78  4705.3 1680.37    4791 1678.84  4835.1 1678.95  4862.9 1677.94
  4920.8 1678.24    4998 1677.15  4998.3 1676.65  5001.8 1676.65    5002 1677.15
  5441.1  1678.1  5581.1 1677.26  5741.7  1678.1  5801.8 1679.02    5849 1678.72
#Mann= 8 ,-1 , 0
  4180.5    .035       0    4357    .045       0  4391.6    .035       0
  4564.4    .045       0  4689.2     .07       0  4705.3    .045       0
    4998    .045       0    5002    .045       0
Bank Sta=4998,5002
XS Rating Curve= 0 ,0
Exp/Cntr=0.3,0.1

Type RM Length L Ch R = 1 ,2890    ,400,400,400
BEGIN DESCRIPTION:
Elm 02 47 4.5
END DESCRIPTION:
XS GIS Cut Line= 3
      1590583.59       6881273.1      1589846.78      6880752.35
      1588954.43      6880664.77
#Sta/Elev= 30
  4107.9 1677.28  4183.3 1676.48  4240.7 1676.56  4282.5 1675.81  4297.3 1676.21
  4318.2  1675.3  4347.6 1675.34  4500.2 1674.65  4606.3 1674.62  4612.5    1674
  4683.8 1673.32  4870.9 1672.61  4921.5  1672.5  4942.4 1671.57  4992.8 1671.25
    4995 1670.02  4998.3 1669.52    5005 1670.02  5007.6 1671.41  5071.7 1671.38
  5163.1 1671.36  5322.3 1671.37  5383.7  1671.3  5464.1 1670.04    5655 1671.63
  5715.2 1673.02  5720.3 1672.39  5755.5 1673.47  5835.9 1672.92  5906.8 1673.34
#Mann= 10 ,-1 , 0
  4107.9     .07       0  4183.3    .045       0  4347.6    .035       0
  4500.2    .045       0  4870.9    .035       0    4995    .035       0
    5005    .035       0  5071.7    .045       0  5163.1    .035       0
  5322.3     .07       0
Bank Sta=4995,5005
XS Rating Curve= 0 ,0
Exp/Cntr=0.3,0.1

Type RM Length L Ch R = 1 ,2490    ,493,493,493
BEGIN DESCRIPTION:
Elm 02 47 4.0
END DESCRIPTION:
XS GIS Cut Line= 3
      1590559.21      6881077.36      1589869.79      6880353.42
      1589199.37      6880250.28
#Sta/Elev= 30
  4084.4 1673.51  4229.5 1672.58  4313.3 1671.42  4475.9 1671.03  4483.2 1670.47
  4773.2 1668.59  4808.4 1669.08  4850.8 1667.92  4978.2 1666.84  4992.4 1666.25
    4998 1663.03  4998.3 1662.53  5001.8 1662.53    5002 1663.03  5006.6 1665.34
  5013.5 1665.19  5041.8 1666.91  5063.2  1666.8  5119.3 1667.72  5159.8 1667.39
    5345 1667.68  5376.4 1667.66  5463.3 1667.09  5509.6 1667.58  5554.4 1665.92
  5616.5 1665.64  5624.4 1665.18  5645.4 1664.02  5723.9 1663.51  5762.4 1663.05
#Mann= 9 ,-1 , 0
  4084.4    .035       0  4229.5    .045       0    4998    .045       0
    5002    .045       0    5345     .07       0  5376.4    .045       0
  5509.6     .07       0  5624.4    .035       0  5723.9     .07       0
Bank Sta=4998,5002
XS Rating Curve= 0 ,0
Exp/Cntr=0.3,0.1

Type RM Length L Ch R = 1 ,1997    ,460,460,460
BEGIN DESCRIPTION:
Elm 02 47 3.0
END DESCRIPTION:
XS GIS Cut Line= 3
      1590626.56      6880684.43      1590245.34      6880048.79
      1589861.32       6879628.1
#Sta/Elev= 30
  4258.8 1667.54  4287.4 1666.99  4293.2 1667.24  4308.8 1666.66  4367.1 1666.27
  4388.5  1666.4  4511.2 1665.36    4542 1665.69  4592.8 1664.76  4759.7 1663.77
  4775.3  1663.3  4818.1 1663.77    4826 1663.64  4833.6 1662.92  4885.8 1662.17
  4934.7 1662.06  4950.2 1661.07    4995 1660.67    4998 1660.54  4998.3 1660.04
  5001.8 1660.04    5002 1660.54  5156.5 1662.06  5191.7 1661.58    5220 1661.97
  5305.1 1662.06    5475 1661.29  5524.7    1662  5531.5 1661.18  5569.6 1660.72
#Mann= 5 ,-1 , 0
  4258.8    .045       0  4885.8    .035       0    4995     .07       0
    4998     .07       0    5002     .07       0
Bank Sta=4998,5002
XS Rating Curve= 0 ,0
Exp/Cntr=0.3,0.1

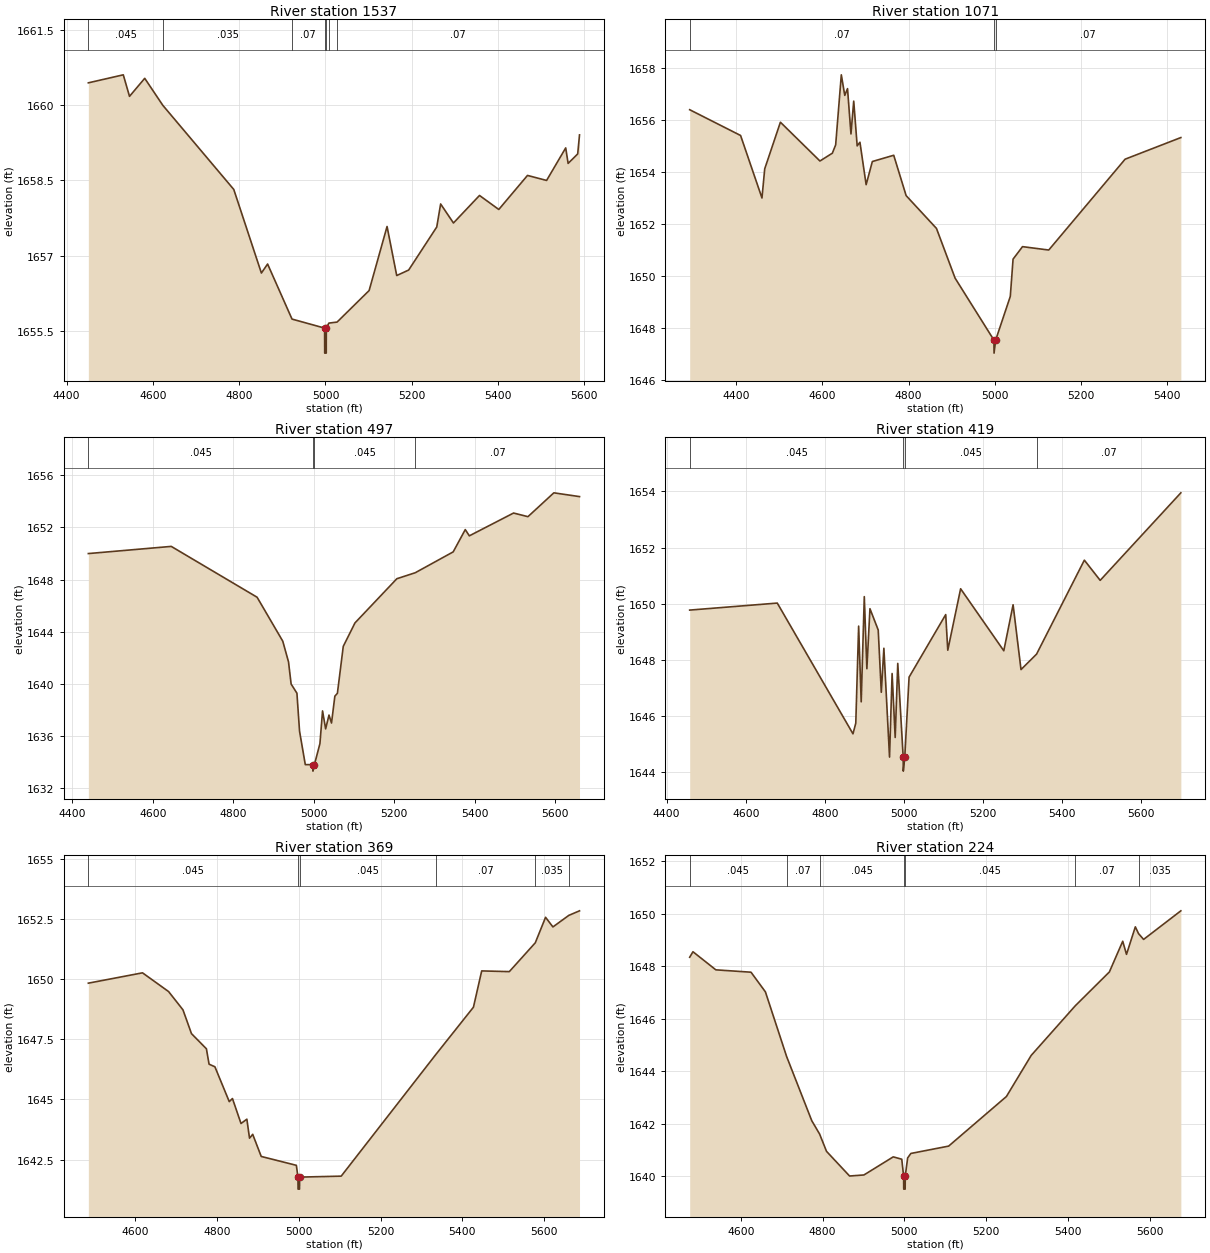
Type RM Length L Ch R = 1 ,1537    ,466,466,466
BEGIN DESCRIPTION:
Elm 02 47 2.5
END DESCRIPTION:
XS GIS Cut Line= 3
       1590919.8      6880197.35       1590442.3      6879601.69
      1590109.02      6879429.61
#Sta/Elev= 30
  4450.4 1660.45  4531.4 1660.61  4545.8 1660.18  4581.1 1660.54  4623.1    1660
  4787.5 1658.32  4851.5 1656.65  4865.9 1656.83  4922.5 1655.73    4998 1655.55
  4998.3 1655.05  5001.8 1655.05    5002 1655.55  5007.9 1655.65  5026.9 1655.67
  5101.2  1656.3  5142.8 1657.58  5165.2  1656.6  5192.9 1656.71    5258 1657.57
    5267 1658.03  5296.7 1657.65  5357.1  1658.2  5401.8 1657.92  5468.3  1658.6
  5512.6  1658.5  5556.9 1659.15  5562.5 1658.84  5584.7 1659.03  5588.9 1659.41
#Mann= 7 ,-1 , 0
  4450.4    .045       0  4623.1    .035       0  4922.5     .07       0
    4998     .07       0    5002     .07       0  5007.9    .035       0
  5026.9     .07       0
Bank Sta=4998,5002
XS Rating Curve= 0 ,0
Exp/Cntr=0.3,0.1

Type RM Length L Ch R = 1 ,1071    ,574,574,574
BEGIN DESCRIPTION:
Elm 02 47 2.0
END DESCRIPTION:
XS GIS Cut Line= 3
       1591366.2      6880022.24      1590888.69      6879426.56
      1590554.46      6879253.99
#Sta/Elev= 30
  4292.1  1656.4  4410.2 1655.41  4459.8 1653.01  4466.2 1654.13  4502.6 1655.92
  4594.3 1654.43  4623.1 1654.73  4630.8 1655.05  4643.9 1657.74  4651.9 1656.95
  4658.3 1657.21  4666.3 1655.47  4672.7 1656.73  4680.7 1655.01  4687.1 1655.15
  4701.5 1653.52  4715.9 1654.41  4765.5 1654.65  4794.3  1653.1  4864.7 1651.84
  4907.9 1649.93    4998 1647.55  4998.3 1647.05    5002 1647.55    5036 1649.23
  5042.4 1650.66  5064.3 1651.14  5125.2 1651.01  5302.4  1654.5  5431.7 1655.33
#Mann= 3 ,-1 , 0
  4292.1     .07       0    4998     .07       0    5002     .07       0
Bank Sta=4998,5002
XS Rating Curve= 0 ,0
Exp/Cntr=0.3,0.1

Type RM Length L Ch R = 1 ,497     ,78,78,78
BEGIN DESCRIPTION:
Elm 02 47 1.0
END DESCRIPTION:
XS GIS Cut Line= 4
       1591647.3      6879385.89      1591199.93      6879012.13
      1591083.23      6879099.39      1590591.25      6879117.76
#Sta/Elev= 30
    4440 1649.99  4646.1 1650.54  4859.5 1646.64  4923.3 1643.27  4937.6 1641.68
  4944.1 1639.98  4958.5 1639.28    4965 1636.37  4979.3  1633.8    4998  1633.8
  4998.3  1633.3    5002  1633.8  5015.7 1635.41  5022.2 1637.92  5029.9 1636.54
  5038.2  1637.6  5044.5 1636.99  5052.8 1639.05  5059.1 1639.27  5073.7 1642.87
  5102.8 1644.67  5206.9 1648.06  5252.7 1648.52    5347 1650.12    5377 1651.83
  5387.1 1651.35  5497.1  1653.1  5532.8 1652.82  5597.2 1654.65    5661 1654.36
#Mann= 4 ,-1 , 0
    4440    .045       0    4998    .045       0    5002    .045       0
  5252.7     .07       0
Bank Sta=4998,5002
XS Rating Curve= 0 ,0
Exp/Cntr=0.3,0.1

Type RM Length L Ch R = 1 ,419     ,50,50,50
BEGIN DESCRIPTION:
Elm 02 47 0.9
END DESCRIPTION:
XS GIS Cut Line= 5
      1591687.16      6879317.21      1591239.79      6878943.45
      1591096.92      6878988.07      1591063.47      6879056.67
      1590631.09      6879049.09
#Sta/Elev= 30
  4458.4 1649.77  4679.8 1650.02  4871.1 1645.36  4878.2 1645.74  4885.4  1649.2
  4891.9  1646.5  4899.7 1650.25  4906.2 1647.68    4914 1649.82  4934.9 1649.06
  4942.7 1646.84  4949.2 1648.41  4963.5 1644.53    4970 1647.51  4977.8 1645.23
  4984.3 1647.87    4998 1644.53  4998.3 1644.03    5002 1644.53  5012.9 1647.38
  5105.5 1649.61  5110.7 1648.34  5143.2 1650.53  5252.3 1648.32  5275.8 1649.96
  5295.8 1647.65  5335.1  1648.2  5455.9 1651.55  5495.9 1650.83  5699.8 1653.95
#Mann= 4 ,-1 , 0
  4458.4    .045       0    4998    .045       0    5002    .045       0
  5335.1     .07       0
Bank Sta=4998,5002
XS Rating Curve= 0 ,0
Exp/Cntr=0.3,0.1

Type RM Length L Ch R = 1 ,369     ,145,145,145
BEGIN DESCRIPTION:
Elm 02 47 0.8
END DESCRIPTION:
XS GIS Cut Line= 5
      1591697.24      6879261.53      1591249.84      6878887.75
      1591053.23      6878912.78      1590826.78      6878948.27
      1590641.87       6878993.2
#Sta/Elev= 30
  4485.6 1649.84    4618 1650.27  4681.8 1649.49  4716.9 1648.73  4737.7 1647.74
  4774.2 1647.11  4780.7 1646.47    4795 1646.36  4830.1 1644.91  4837.9 1645.04
  4858.8    1644  4873.1 1644.18  4879.6 1643.39  4887.4 1643.55  4908.2 1642.63
  4994.1 1642.26    4998 1641.77  4998.3 1641.27  5001.8 1641.27    5002 1641.77
  5103.7 1641.81    5335 1646.87    5427 1648.84  5447.2 1650.35  5514.7 1650.32
  5578.2 1651.52  5603.3 1652.58  5621.3 1652.18  5660.1 1652.66  5686.3 1652.85
#Mann= 6 ,-1 , 0
  4485.6    .045       0    4998    .045       0    5002    .045       0
    5335     .07       0  5578.2    .035       0  5660.1     .07       0
Bank Sta=4998,5002
XS Rating Curve= 0 ,0
Exp/Cntr=0.3,0.1

Type RM Length L Ch R = 1 ,224     ,0,0,0
BEGIN DESCRIPTION:
Elm 02 47 0.5
END DESCRIPTION:
XS GIS Cut Line= 5
      1591781.57      6879151.91      1591334.17      6878778.13
      1591137.56      6878803.16      1590911.11      6878838.65
      1590726.97      6878883.39
#Sta/Elev= 30
  4475.4 1648.34  4483.4 1648.55  4539.3 1647.86  4625.2 1647.77  4660.4 1647.02
  4712.1 1644.56  4773.6 1642.11  4792.8  1641.6  4809.7 1640.94    4866    1640
  4901.1 1640.04  4972.7 1640.73  4993.5 1640.64    4998    1640  4998.3  1639.5
  5001.8  1639.5    5002    1640  5007.9 1640.69  5015.7 1640.86    5108 1641.14
  5249.1 1643.03  5309.8  1644.6  5417.4 1646.49  5500.7 1647.78  5533.3 1648.95
  5542.5 1648.45  5564.1  1649.5    5572 1649.24  5584.3 1649.02  5675.3 1650.11
#Mann= 7 ,-1 , 0
  4475.4    .045       0  4712.1     .07       0  4792.8    .045       0
    4998    .045       0    5002    .045       0  5417.4     .07       0
    5572    .035       0
Bank Sta=4998,5002
XS Rating Curve= 0 ,0
Exp/Cntr=0.3,0.1

Chan Stop Cuts=-1
Use User Specified Reach Order=0
Composite Channel Slope=5