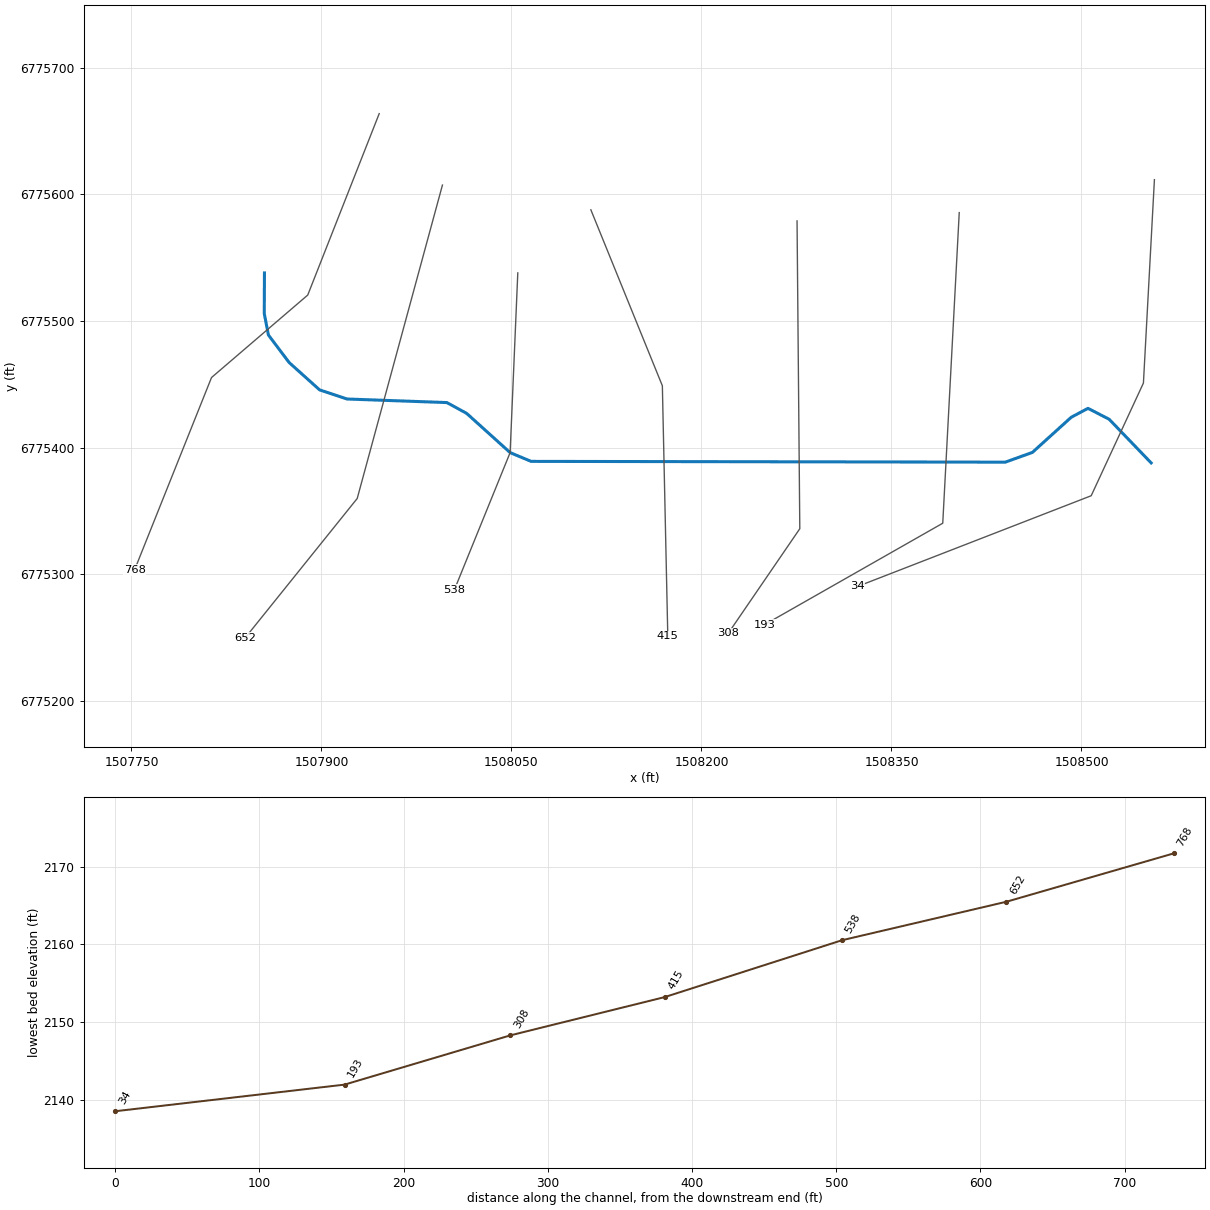
--- Elm 02 61.prj (project) ---

Proj Title=Elm 02 61 Base Level Engineering
Current Plan=p01
Default Exp/Contr=0.3,0.1
English Units
Geom File=g01
Flow File=f01
Plan File=p01
BEGIN DESCRIPTION:
Elm 02 61
END DESCRIPTION:

--- Elm 02 61.p01 (plan) ---

Plan Title=Multiple Run
Short Identifier=Multiple
Geom File=g01
Flow File=f01
Subcritical Flow
K Sum by GR= 0
Std Step Tol= 0.01
Critical Tol= 0.01
Num of Std Step Trials= 20
Max Error Tol= 0.3
Flow Tol Ratio= 0.001
Split Flow NTrial= 30
Split Flow Tol= 0.02
Split Flow Ratio= 0.02
Log Output Level= 0
Friction Slope Method= 1
Unsteady Friction Slope Method= 2
Unsteady Bridges Friction Slope Method= 1
Parabolic Critical Depth
Global Vel Dist=  1 , 1 , 1
Global Log Level= 0
CheckData=True
Encroach Param= -1, 0, 0, 0
BEGIN DESCRIPTION:
Multiple Run
END DESCRIPTION:

--- Elm 02 61.f01 (steady flow) ---

Flow Title=Multiple
Number of Profiles=7
Profile Names=10-year,25-year,50-year,1pct_min,100-year,1pct_plu,500-year
River Rch & RM= Elm 02 61,Reach-1,768
      42      52      59      42      68      94      90
River Rch & RM= Elm 02 61,Reach-1,34
     139     188     228     173     277     381     411
Boundary for River Rch & Prof#=Elm 02 61,Reach-1,1
Up Type=0
Dn Type=3
Dn Slope=0.005
Boundary for River Rch & Prof#=Elm 02 61,Reach-1,2
Up Type=0
Dn Type=3
Dn Slope=0.005
Boundary for River Rch & Prof#=Elm 02 61,Reach-1,3
Up Type=0
Dn Type=3
Dn Slope=0.005
Boundary for River Rch & Prof#=Elm 02 61,Reach-1,4
Up Type=0
Dn Type=3
Dn Slope=0.005
Boundary for River Rch & Prof#=Elm 02 61,Reach-1,5
Up Type=0
Dn Type=3
Dn Slope=0.005
Boundary for River Rch & Prof#=Elm 02 61,Reach-1,6
Up Type=0
Dn Type=3
Dn Slope=0.005
Boundary for River Rch & Prof#=Elm 02 61,Reach-1,7
Up Type=0
Dn Type=3
Dn Slope=0.005

--- Elm 02 61.g01 (geometry) ---

Geom Title=Existing Conditions

River Reach=Elm 02 61,Reach-1
Reach XY= 19
      1507855.00      6775538.00      1507854.85      6775505.93
      1507858.12      6775488.99      1507874.50      6775467.24
      1507898.55      6775445.64      1507920.11      6775438.46
      1507999.02      6775435.64      1508014.63      6775427.10
      1508048.94      6775396.14      1508065.50      6775389.22
      1508159.09      6775389.06      1508252.68      6775388.91
      1508346.26      6775388.76      1508439.85      6775388.60
      1508461.22      6775396.29      1508491.89      6775424.03
      1508505.14      6775431.09      1508521.84      6775422.46
      1508555.00      6775388.00

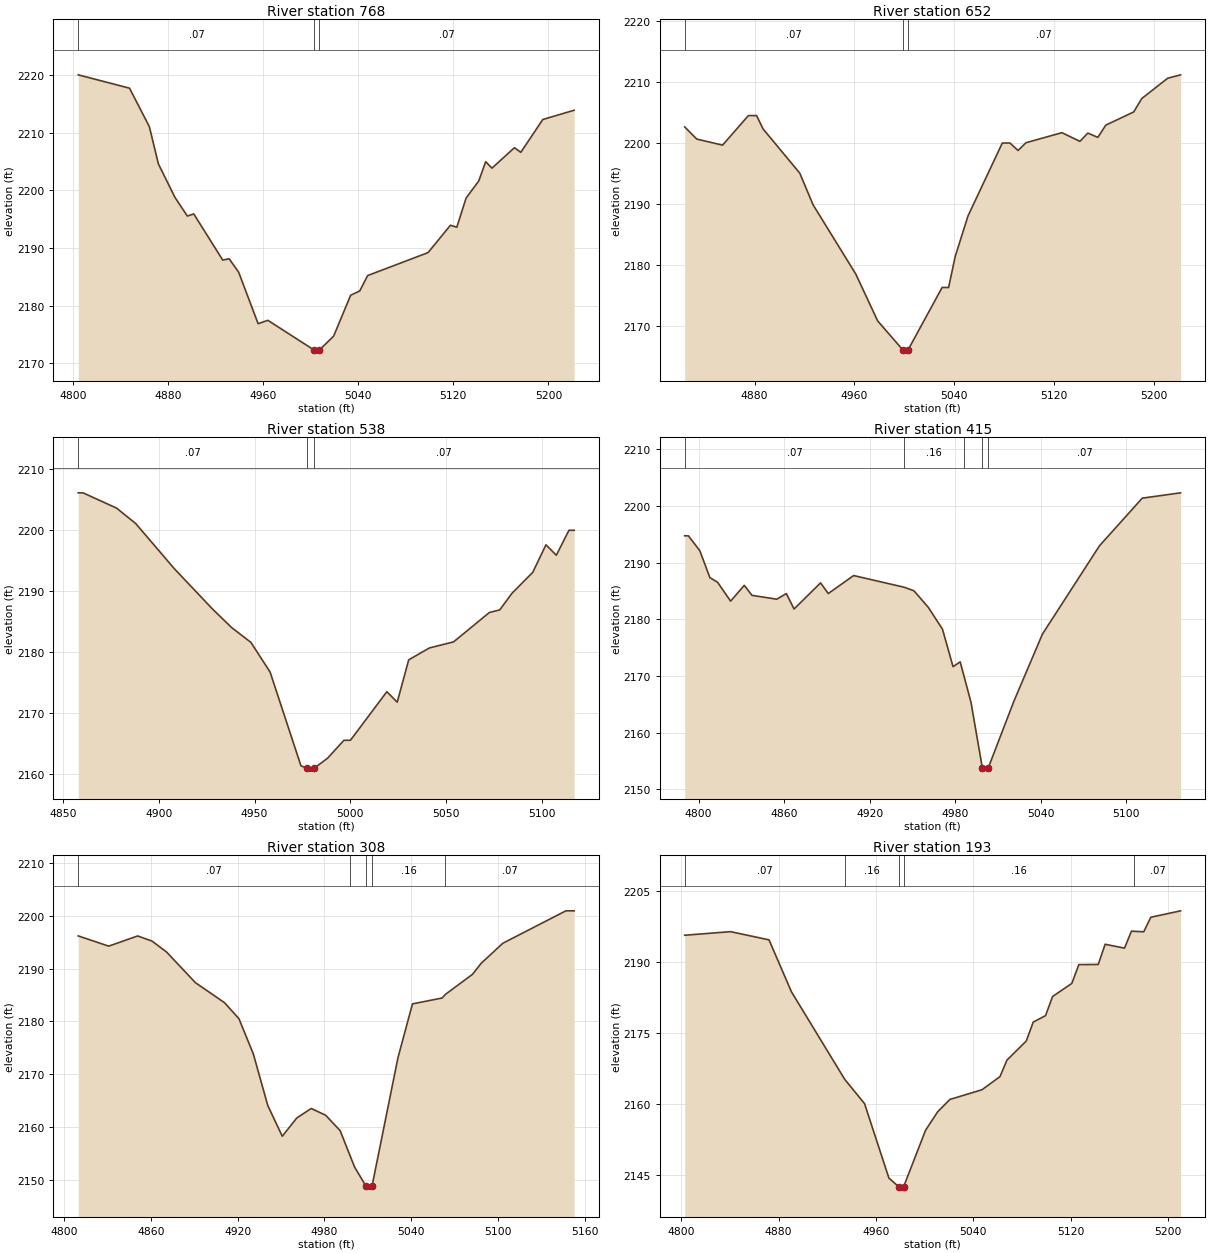
Type RM Length L Ch R = 1,768,116,116,116
BEGIN DESCRIPTION:
elmc232
END DESCRIPTION:
XS GIS Cut Line= 4
      1507945.59      6775663.73      1507889.17      6775520.51
      1507813.21      6775455.40      1507752.44      6775303.48
#Sta/Elev= 30
  4804.1 2220.08  4847.3 2217.76  4864.0 2211.08  4871.6 2204.62  4885.5 2198.81
  4896.0 2195.55  4901.4 2195.92  4925.8 2187.90  4931.2 2188.13  4939.2 2185.80
  4955.6 2176.85  4963.8 2177.44  5003.0 2172.24  5003.2 2171.74  5007.0 2172.24
  5019.2 2174.70  5033.5 2181.79  5041.2 2182.55  5047.8 2185.21  5098.7 2189.20
  5117.5 2193.95  5122.9 2193.61  5130.7 2198.67  5141.4 2201.65  5147.2 2204.99
  5152.5 2203.87  5171.4 2207.42  5176.8 2206.62  5195.3 2212.32  5221.7 2213.93
#Mann=3,-1,0
  4804.1    0.07       0  5003.0    0.07       0  5007.0    0.07       0
Bank Sta=5003,5007
Exp/Cntr=0.3,0.1

Type RM Length L Ch R = 1,652,114,114,114
BEGIN DESCRIPTION:
elmc231
END DESCRIPTION:
XS GIS Cut Line= 3
      1507995.51      6775607.35      1507928.23      6775359.92
      1507839.64      6775249.73
#Sta/Elev= 30
  4823.9 2202.58  4833.6 2200.58  4854.3 2199.59  4875.0 2204.43  4881.6 2204.43
  4886.8 2202.24  4916.2 2195.01  4926.9 2189.81  4961.2 2178.45  4978.7 2170.79
  4999.0 2166.01  4999.2 2165.51  5003.0 2166.01  5030.4 2176.27  5035.6 2176.26
  5040.9 2181.35  5051.2 2188.01  5078.7 2199.94  5084.8 2199.94  5091.3 2198.71
  5097.7 2199.99  5126.5 2201.63  5140.9 2200.21  5147.3 2201.56  5155.3 2200.86
  5161.7 2202.87  5184.1 2205.03  5190.5 2207.22  5211.3 2210.55  5221.7 2211.11
#Mann=3,-1,0
  4823.9    0.07       0  4999.0    0.07       0  5003.0    0.07       0
Bank Sta=4999,5003
Exp/Cntr=0.3,0.1

Type RM Length L Ch R = 1,538,123,123,123
BEGIN DESCRIPTION:
elmc218
END DESCRIPTION:
XS GIS Cut Line= 3
      1508055.00      6775538.01      1508048.94      6775396.14
      1508005.01      6775288.02
#Sta/Elev= 30
  4858.0 2206.12  4860.5 2206.12  4878.0 2203.62  4888.0 2201.09  4908.1 2193.71
  4928.1 2187.08  4938.1 2184.04  4948.1 2181.63  4958.1 2176.77  4974.2 2161.41
  4977.2 2161.05  4977.4 2160.55  4980.9 2160.55  4981.2 2161.05  4988.1 2162.67
  4996.6 2165.60  5000.0 2165.60  5019.0 2173.56  5024.4 2171.84  5030.4 2178.77
  5041.2 2180.72  5053.8 2181.71  5072.5 2186.53  5077.9 2186.95  5084.3 2189.68
  5095.1 2193.10  5102.0 2197.61  5107.4 2195.90  5114.0 2199.99  5116.7 2199.99
#Mann=3,-1,0
  4858.0    0.07       0  4977.2    0.07       0  4981.2    0.07       0
Bank Sta=4977.2,4981.2
Exp/Cntr=0.3,0.1

Type RM Length L Ch R = 1,415,107,107,107
BEGIN DESCRIPTION:
elmc230
END DESCRIPTION:
XS GIS Cut Line= 3
      1508112.68      6775587.81      1508169.12      6775448.89
      1508173.42      6775251.08
#Sta/Elev= 30
  4790.2 2194.72  4792.8 2194.72  4800.8 2192.10  4807.9 2187.34  4813.3 2186.52
  4822.4 2183.20  4832.0 2185.98  4837.4 2184.22  4854.8 2183.54  4861.5 2184.53
  4866.9 2181.81  4885.5 2186.42  4890.9 2184.54  4908.7 2187.71  4944.3 2185.64
  4951.0 2185.02  4961.0 2182.12  4971.0 2178.25  4978.4 2171.64  4983.4 2172.49
  4985.8 2170.24  4991.0 2165.35  4999.0 2153.72  4999.3 2153.22  5003.0 2153.72
  5021.0 2165.50  5041.1 2177.39  5081.1 2192.96  5111.1 2201.36  5138.0 2202.30
#Mann=5,-1,0
  4790.2    0.07       0  4944.3    0.16       0  4985.8    0.07       0
  4999.0    0.07       0  5003.0    0.07       0
Bank Sta=4999,5003
Exp/Cntr=0.3,0.1

Type RM Length L Ch R = 1,308,115,115,115
BEGIN DESCRIPTION:
elmc229
END DESCRIPTION:
XS GIS Cut Line= 3
      1508275.45      6775579.06      1508277.62      6775336.05
      1508221.22      6775253.62
#Sta/Elev= 30
  4809.8 2196.18  4830.9 2194.24  4850.9 2196.17  4860.9 2195.19  4870.9 2193.13
  4890.9 2187.32  4910.9 2183.56  4920.9 2180.54  4930.9 2173.84  4940.9 2164.08
  4950.9 2158.29  4960.9 2161.74  4970.9 2163.54  4980.9 2162.26  4990.9 2159.35
  4998.0 2154.46  5000.9 2152.46  5008.9 2148.79  5009.1 2148.29  5012.6 2148.29
  5012.9 2148.79  5030.9 2173.16  5040.9 2183.32  5061.4 2184.43  5063.7 2185.12
  5082.4 2188.91  5088.4 2190.99  5103.4 2194.79  5147.0 2200.92  5152.7 2200.92
#Mann=5,-1,0
  4809.8    0.07       0  4998.0    0.16       0  5008.9    0.07       0
  5012.9    0.16       0  5063.7    0.07       0
Bank Sta=5008.9,5012.9
Exp/Cntr=0.3,0.1

Type RM Length L Ch R = 1,193,159,159,159
BEGIN DESCRIPTION:
elmc228
END DESCRIPTION:
XS GIS Cut Line= 3
      1508403.49      6775585.60      1508390.47      6775340.39
      1508249.73      6775260.28
#Sta/Elev= 30
  4802.8 2195.56  4840.5 2196.32  4872.1 2194.59  4890.5 2183.63  4934.3 2165.13
  4950.6 2160.00  4970.6 2144.28  4978.7 2142.44  4978.9 2141.94  4982.7 2142.44
  5000.7 2154.36  5010.7 2158.28  5020.7 2160.88  5047.1 2162.93  5061.9 2165.71
  5067.6 2169.19  5083.5 2173.23  5089.2 2177.22  5099.3 2178.58  5105.1 2182.62
  5120.9 2185.39  5126.7 2189.36  5142.6 2189.39  5148.3 2193.66  5164.2 2192.84
  5169.9 2196.42  5172.4 2196.39  5180.0 2196.29  5185.8 2199.36  5210.3 2200.72
#Mann=5,-1,0
  4802.8    0.07       0  4934.3    0.16       0  4978.7    0.07       0
  4982.7    0.16       0  5172.4    0.07       0
Bank Sta=4978.7,4982.7
Exp/Cntr=0.3,0.1

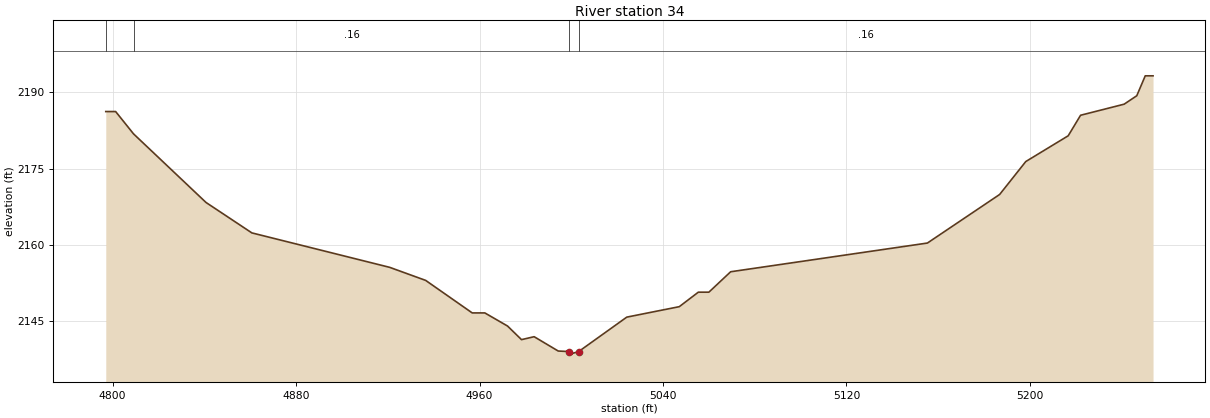
Type RM Length L Ch R = 1,34,0,0,0
BEGIN DESCRIPTION:
elmc227
END DESCRIPTION:
XS GIS Cut Line= 4
      1508557.57      6775611.64      1508548.89      6775451.06
      1508507.66      6775362.09      1508323.24      6775290.49
#Sta/Elev= 30
  4797.0 2186.25  4801.3 2186.25  4809.1 2181.86  4840.7 2168.36  4860.7 2162.37
  4920.8 2155.59  4936.5 2153.02  4956.8 2146.62  4962.3 2146.62  4972.2 2144.04
  4978.3 2141.36  4983.8 2141.94  4994.3 2139.12  4999.2 2139.01  4999.5 2138.51
  5003.2 2139.01  5024.2 2145.79  5047.1 2147.85  5055.4 2150.70  5060.0 2150.70
  5069.5 2154.72  5155.3 2160.37  5186.8 2169.93  5198.2 2176.41  5216.7 2181.48
  5222.1 2185.52  5241.1 2187.70  5246.6 2189.36  5250.3 2193.28  5253.7 2193.28
#Mann=4,-1,0
  4797.0    0.07       0  4809.1    0.16       0  4999.2    0.07       0
  5003.2    0.16       0
Bank Sta=4999.2,5003.2
Exp/Cntr=0.3,0.1

Chan Stop Cuts=-1