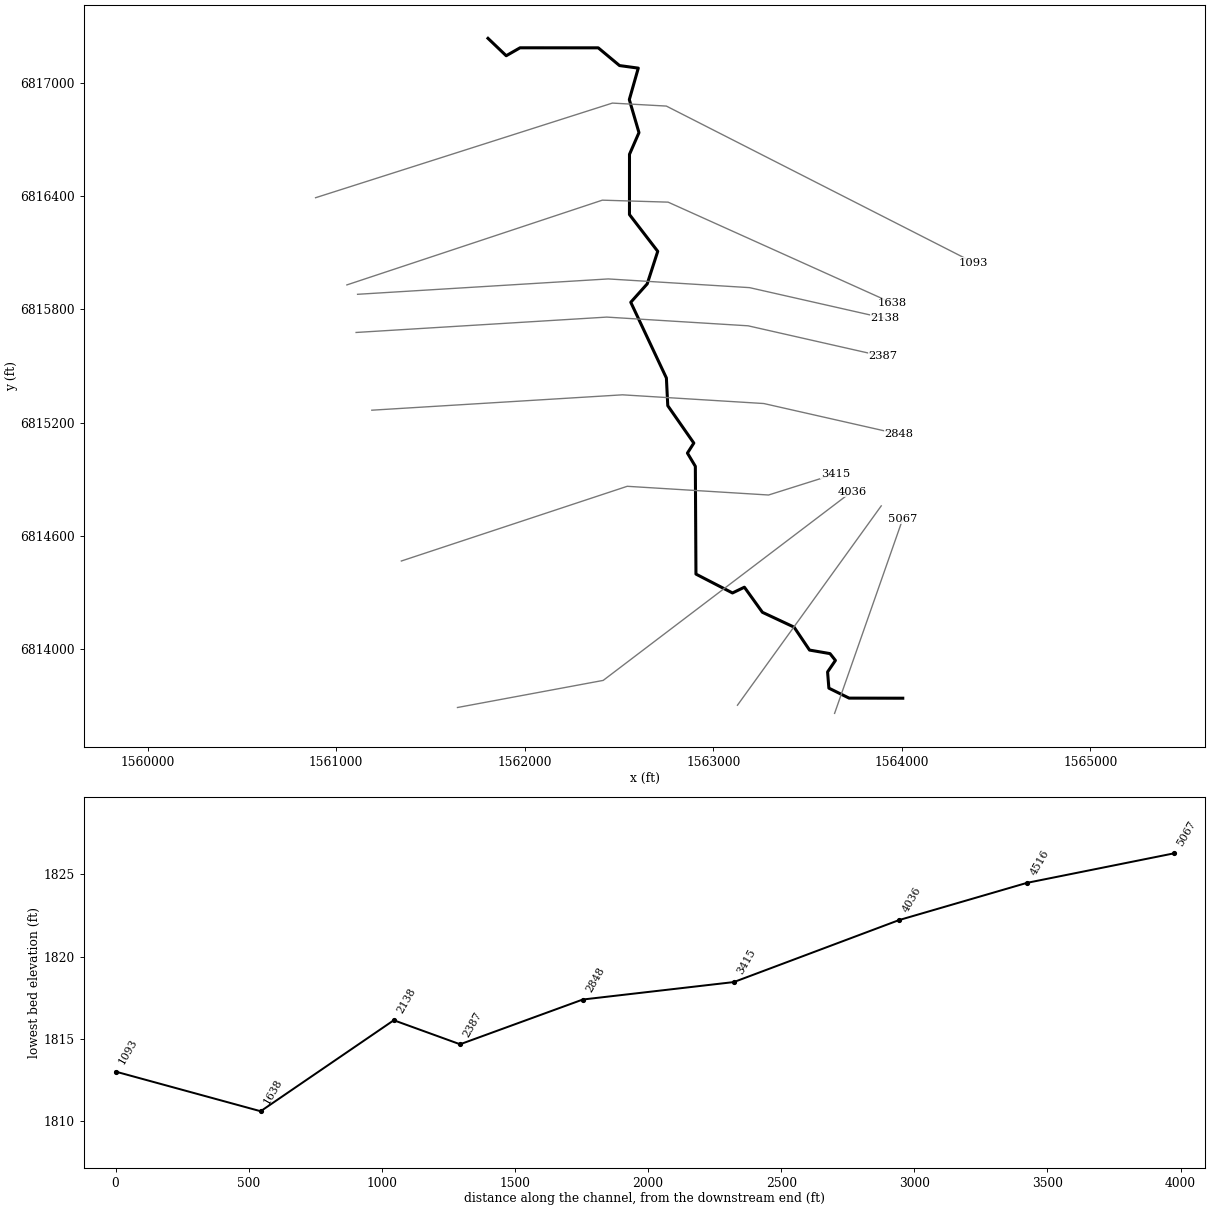
--- Elm 02 62.prj (project) ---

Proj Title=Elm 02 62 Base Level Engineering
Current Plan=p01
Default Exp/Contr=0.3,0.1
English Units
Geom File=g01
Flow File=f01
Plan File=p01
Y Axis Title=Elevation
X Axis Title(PF)=Main Channel Distance
X Axis Title(XS)=Station
BEGIN DESCRIPTION:
Elm 02 62
END DESCRIPTION:
DSS Export Rating Curves= 0
DSS Export Rating Curve Sorted= 0
DSS Export Volume Flow Curves= 0
DXF OffsetX= 0
DXF OffsetY= 0
DXF ScaleX= 1
DXF ScaleY= 10

--- Elm 02 62.p01 (plan) ---

Plan Title=Multiple Run
Program Version=4.10
Short Identifier=Multiple
Geom File=g01
Flow File=f01
Subcritical Flow
K Sum by GR= 0
Std Step Tol= 0.01
Critical Tol= 0.01
Num of Std Step Trials= 20
Max Error Tol= 0.3
Flow Tol Ratio= 0.001
Split Flow NTrial= 30
Split Flow Tol= 0.02
Split Flow Ratio= 0.02
Log Output Level= 0
Friction Slope Method= 1
Unsteady Friction Slope Method= 2
Unsteady Bridges Friction Slope Method= 1
Parabolic Critical Depth
Global Vel Dist= 1 , 1 , 1
Global Log Level= 0
CheckData=True
Encroach Param=-1 ,0,0, 0
BEGIN DESCRIPTION:
Multiple Run
END DESCRIPTION:
Computation Interval=1HOUR
Output Interval=1HOUR
Run HTab= 0
Run UNet= 0
Run PostProcess= 0
Run WQNet= 0
UNET Theta= 1
UNET Theta Warmup= 1
UNET ZTol= 0.02
UNET ZSATol= 0.05
UNET MxIter= 20
UNET MaxInSteps= 0
UNET DtIC= 0
UNET DtMin= 0
UNET MaxCRTS= 20
UNET WFStab= 2
UNET SFStab= 1
UNET WFX= 1
UNET SFX= 1
UNET DSS MLevel= 4
UNET DZMax Abort= 100
UNET Convert EG Bridges= 0
UNET Use Existing IB Tables=-1
UNET Froude Reduction=False
UNET Froude Limit= 1
UNET Froude Power= 10
UNET Time Slicing=0,0, 5
UNET Junction Losses=0
Instantaneous Interval=1HOUR
Write IC File= 0
Write IC File at Sim End=0
Echo Input=False
Echo Parameters=False
Echo Output=False
Write Detailed= 0
WQ AD Non Conservative
WQ ULTIMATE=-1
WQ Max Comp Step=1HOUR
WQ Output Interval=15MIN
WQ Output Selected Increments= 0
WQ Output face flow=0
WQ Output face velocity=0
WQ Output face area=0
WQ Output face dispersion=0
WQ Output cell volume=0
WQ Output cell surface area=0
WQ Output cell continuity=0
WQ Output cumulative cell continuity=0
WQ Output face conc=0
WQ Output face dconc_dx=0
WQ Output face courant=0
WQ Output face peclet=0
WQ Output face adv mass=0
WQ Output face disp mass=0
WQ Output cell mass=0
WQ Output cell source sink temp=0
WQ Output cell source sink nsm=0
WQ Output MaxMinRange=-1
WQ Daily Max Min Mean=-1
WQ Daily Range=0
WQ Daily Time=0
WQ Create Restart=0
WQ Fixed Restart=0
WQ System Summary=0
WQ Use Fixed Temperature=0
Sorting and Armoring Iterations= 10
XS Update Threshold= 0.02
Hydraulics Update Threshold= 0.02
Energy Slope Method= 1
Volume Change Method= 0
XS Weighting Method= 0
Number of US Weighted Cross Sections= 1
Number of DS Weighted Cross Sections= 1
Upstream XS Weight=0.25
Main XS Weight=0.5
Downstream XS Weight=0.25
Number of DS XS's Weighted with US Boundary= 1
Upstream Boundary Weight= 1
Weight of XSs Associated with US Boundary= 0
Number of US XS's Weighted with DS Boundary= 1
Downstream Boundary Weight= 0.5
Weight of XSs Associated with DS Boundary= 0.5
Sediment Output Level= 4
Mass or Volume Output= 0
Output Increment Type= 1
Profile and TS Output Increment= 10
XS Output Flag= 0
XS Output Increment= 10
Disregard all LS=0
Disregard all Conn=0
Disregard all Breaches=0
Disregard all Pumps=0

--- Elm 02 62.f01 (steady flow) ---

Flow Title=Multiple
Number of Profiles=7
Profile Names=10-year,25-year,50-year,1pct_min,100-year,1pct_plu,500-year
River Rch & RM= Elm 02 62,Reach-1,5067
      51      62      70      40      80     159     102
Boundary for River Rch & Prof#=Elm 02 62,Reach-1,1
Up Type=0
Dn Type=3
Dn Slope=0.005
Boundary for River Rch & Prof#=Elm 02 62,Reach-1,2
Up Type=0
Dn Type=3
Dn Slope=0.005
Boundary for River Rch & Prof#=Elm 02 62,Reach-1,3
Up Type=0
Dn Type=3
Dn Slope=0.005
Boundary for River Rch & Prof#=Elm 02 62,Reach-1,4
Up Type=0
Dn Type=3
Dn Slope=0.005
Boundary for River Rch & Prof#=Elm 02 62,Reach-1,5
Up Type=0
Dn Type=3
Dn Slope=0.005
Boundary for River Rch & Prof#=Elm 02 62,Reach-1,6
Up Type=0
Dn Type=3
Dn Slope=0.005
Boundary for River Rch & Prof#=Elm 02 62,Reach-1,7
Up Type=0
Dn Type=3
Dn Slope=0.005

--- Elm 02 62.g01 (geometry) ---

Geom Title=Existing Conditions

River Reach=Elm 02 62,Reach-1
Reach XY= 30
      1564005.00      6813738.00      1563720.19      6813738.50
      1563613.03      6813791.37      1563606.23      6813877.42
      1563647.78      6813938.34      1563619.09      6813974.59
      1563510.48      6813993.26      1563428.51      6814115.01
      1563260.61      6814193.60      1563165.02      6814326.77
      1563101.77      6814296.25      1562908.06      6814396.28
      1562904.82      6814968.02      1562862.80      6815038.10
      1562896.76      6815091.23      1562758.55      6815289.47
      1562751.24      6815436.44      1562562.30      6815838.08
      1562649.45      6815935.57      1562705.36      6816108.21
      1562555.38      6816303.16      1562555.52      6816622.78
      1562605.82      6816738.00      1562554.60      6816913.00
      1562602.16      6817079.99      1562502.65      6817093.57
      1562389.84      6817187.61      1561974.98      6817187.81
      1561901.58      6817145.68      1561805.00      6817238.00

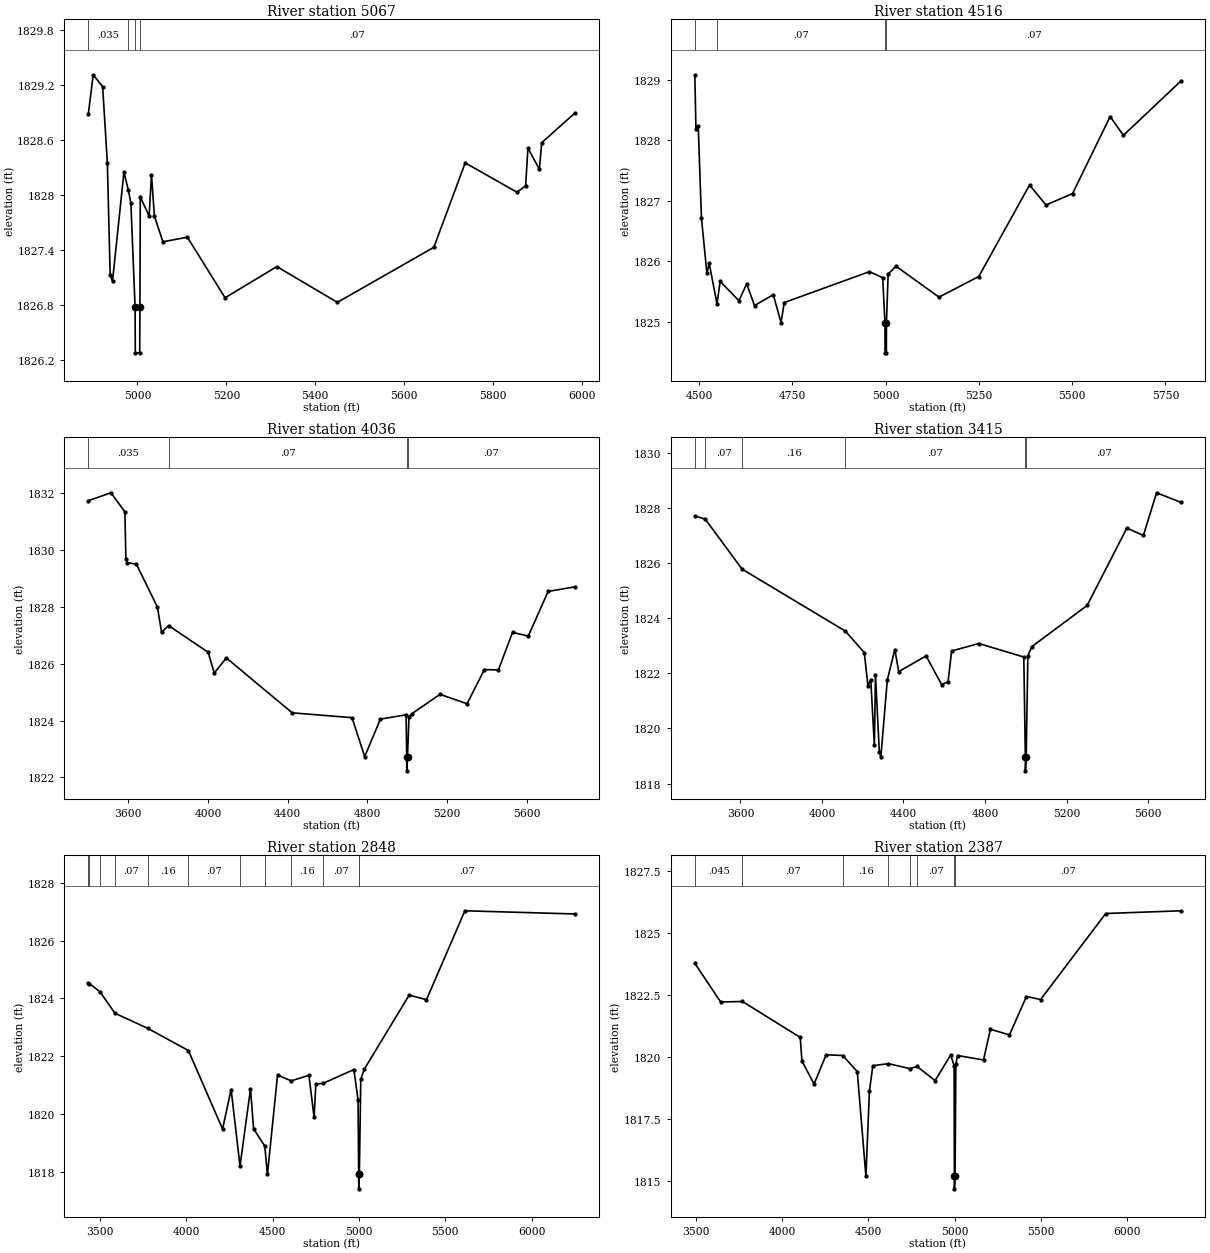
Type RM Length L Ch R = 1,5067,551,551,551
BEGIN DESCRIPTION:
Elm 02 62 9.0
END DESCRIPTION:
XS GIS Cut Line= 2
      1563643.40      6813657.56      1564005.33      6814690.27
#Sta/Elev= 30
  4889.3 1828.88  4900.4 1829.31  4921.6 1829.18  4932.2 1828.35  4938.5 1827.13
  4943.8 1827.06  4969.5 1828.25  4979.6 1828.05  4985.1 1827.91  4994.6 1826.78
  4995.1 1826.28  5005.0 1826.28  5005.5 1826.78  5006.3 1827.98  5026.2 1827.77
  5031.5 1828.22  5038.1 1827.77  5057.2 1827.49  5112.3 1827.54  5197.1 1826.88
  5313.6 1827.22  5449.8 1826.83  5666.9 1827.43  5737.5 1828.35  5854.0 1828.03
  5873.4 1828.10  5878.7 1828.51  5904.4 1828.28  5909.7 1828.57  5983.6 1828.89
#Mann=4,-1,0
  4889.3   0.035       0  4979.6    0.07       0  4994.6    0.07       0
  5005.5    0.07       0
Bank Sta=4994.6,5005.5
Exp/Cntr=0.3,0.1

Type RM Length L Ch R = 1,4516,480,480,480
BEGIN DESCRIPTION:
Elm 02 62 8.0
END DESCRIPTION:
XS GIS Cut Line= 2
      1563128.15      6813700.78      1563890.80      6814758.13
#Sta/Elev= 30
  4488.3 1829.08  4491.3 1828.18  4497.4 1828.24  4506.0 1826.72  4520.7 1825.80
  4526.8 1825.97  4547.7 1825.30  4556.3 1825.67  4606.6 1825.35  4627.4 1825.63
  4648.3 1825.27  4698.6 1825.45  4719.5 1824.99  4728.0 1825.32  4956.3 1825.83
  4991.9 1825.73  4998.0 1824.99  4998.3 1824.49  5001.8 1824.49  5002.0 1824.99
  5006.6 1825.79  5027.5 1825.92  5142.8 1825.41  5249.6 1825.75  5385.7 1827.26
  5429.9 1826.93  5501.1 1827.12  5601.7 1828.39  5637.3 1828.08  5792.0 1828.98
#Mann=4,-1,0
  4488.3   0.035       0  4547.7    0.07       0  4998.0    0.07       0
  5002.0    0.07       0
Bank Sta=4998,5002
Exp/Cntr=0.3,0.1

Type RM Length L Ch R = 1,4036,621,621,621
BEGIN DESCRIPTION:
Elm 02 62 7.0
END DESCRIPTION:
XS GIS Cut Line= 3
      1561643.18      6813688.69      1562416.04      6813832.44
      1563735.02      6814833.89
#Sta/Elev= 30
  3398.8 1831.73  3512.5 1832.01  3582.6 1831.34  3587.6 1829.69  3593.9 1829.55
  3640.4 1829.50  3745.9 1827.99  3766.8 1827.10  3801.9 1827.34  4000.8 1826.40
  4031.3 1825.67  4092.3 1826.20  4422.9 1824.27  4723.5 1824.10  4786.9 1822.73
  4865.9 1824.05  4994.8 1824.20  4998.0 1822.73  4998.3 1822.23  5002.0 1822.73
  5009.3 1824.12  5023.9 1824.24  5165.4 1824.92  5301.1 1824.59  5387.9 1825.79
  5458.6 1825.78  5529.3 1827.10  5608.4 1826.97  5708.2 1828.54  5841.0 1828.70
#Mann=4,-1,0
  3398.8   0.035       0  3801.9    0.07       0  4998.0    0.07       0
  5002.0    0.07       0
Bank Sta=4998,5002
Exp/Cntr=0.3,0.1

Type RM Length L Ch R = 1,3415,567,567,567
BEGIN DESCRIPTION:
Elm 02 62 6.0
END DESCRIPTION:
XS GIS Cut Line= 4
      1561345.52      6814465.76      1562543.54      6814861.98
      1563293.16      6814815.78      1563648.81      6814927.95
#Sta/Elev= 30
  3376.3 1827.71  3427.9 1827.59  3608.0 1825.78  4115.0 1823.53  4207.8 1822.75
  4225.5 1821.55  4239.4 1821.77  4257.2 1819.39  4262.5 1821.95  4281.6 1819.14
  4289.0 1818.96  4320.7 1821.76  4357.7 1822.86  4376.4 1822.06  4511.0 1822.63
  4587.0 1821.59  4618.6 1821.69  4636.3 1822.81  4769.9 1823.08  4990.3 1822.59
  4998.0 1818.96  4998.3 1818.46  5002.0 1818.96  5010.3 1822.64  5030.3 1822.97
  5300.9 1824.46  5496.0 1827.27  5577.0 1827.00  5641.7 1828.55  5762.1 1828.20
#Mann=6,-1,0
  3376.3   0.045       0  3427.9    0.07       0  3608.0    0.16       0
  4115.0    0.07       0  4998.0    0.07       0  5002.0    0.07       0
Bank Sta=4998,5002
Exp/Cntr=0.3,0.1

Type RM Length L Ch R = 1,2848,461,461,461
BEGIN DESCRIPTION:
Elm 02 62 5.0
END DESCRIPTION:
XS GIS Cut Line= 4
      1561188.87      6815265.64      1562518.36      6815347.18
      1563267.97      6815300.98      1563984.89      6815138.58
#Sta/Elev= 30
  3431.1 1824.53  3437.7 1824.51  3499.3 1824.22  3585.8 1823.48  3775.0 1822.96
  4011.3 1822.19  4209.2 1819.47  4258.8 1820.84  4310.3 1818.19  4371.1 1820.86
  4389.0 1819.48  4453.9 1818.88  4469.2 1817.90  4527.9 1821.34  4607.1 1821.14
  4709.6 1821.33  4739.7 1819.88  4749.7 1821.02  4794.0 1821.06  4970.1 1821.53
  4994.4 1820.48  4998.0 1817.90  4998.3 1817.40  5002.0 1817.90  5010.2 1821.19
  5030.2 1821.54  5290.7 1824.11  5390.9 1823.95  5613.6 1827.03  6249.2 1826.92
#Mann=12,-1,0
  3431.1   0.045       0  3437.7    0.07       0  3499.3   0.045       0
  3585.8    0.07       0  3775.0    0.16       0  4011.3    0.07       0
  4310.3    0.16       0  4453.9    0.07       0  4607.1    0.16       0
  4794.0    0.07       0  4998.0    0.07       0  5002.0    0.07       0
Bank Sta=4998,5002
Exp/Cntr=0.3,0.1

Type RM Length L Ch R = 1,2387,249,249,249
BEGIN DESCRIPTION:
Elm 02 62 4.0
END DESCRIPTION:
XS GIS Cut Line= 4
      1561105.52      6815677.92      1562434.95      6815759.45
      1563184.56      6815713.25      1563900.76      6815551.01
#Sta/Elev= 30
  3494.3 1823.78  3644.1 1822.22  3770.3 1822.24  4104.9 1820.79  4114.9 1819.84
  4185.1 1818.91  4255.2 1820.09  4351.5 1820.06  4435.5 1819.41  4485.6 1815.18
  4505.7 1818.61  4525.7 1819.65  4615.9 1819.73  4741.3 1819.53  4781.0 1819.62
  4886.4 1819.05  4976.6 1820.08  4996.6 1819.65  4998.0 1815.18  4998.3 1814.68
  5002.0 1815.18  5006.6 1819.71  5016.6 1820.06  5166.9 1819.88  5207.0 1821.12
  5317.2 1820.89  5415.5 1822.44  5497.5 1822.32  5875.1 1825.79  6311.6 1825.90
#Mann=8,-1,0
  3494.3   0.045       0  3770.3    0.07       0  4351.5    0.16       0
  4615.9    0.07       0  4741.3    0.16       0  4781.0    0.07       0
  4998.0    0.07       0  5002.0    0.07       0
Bank Sta=4998,5002
Exp/Cntr=0.3,0.1

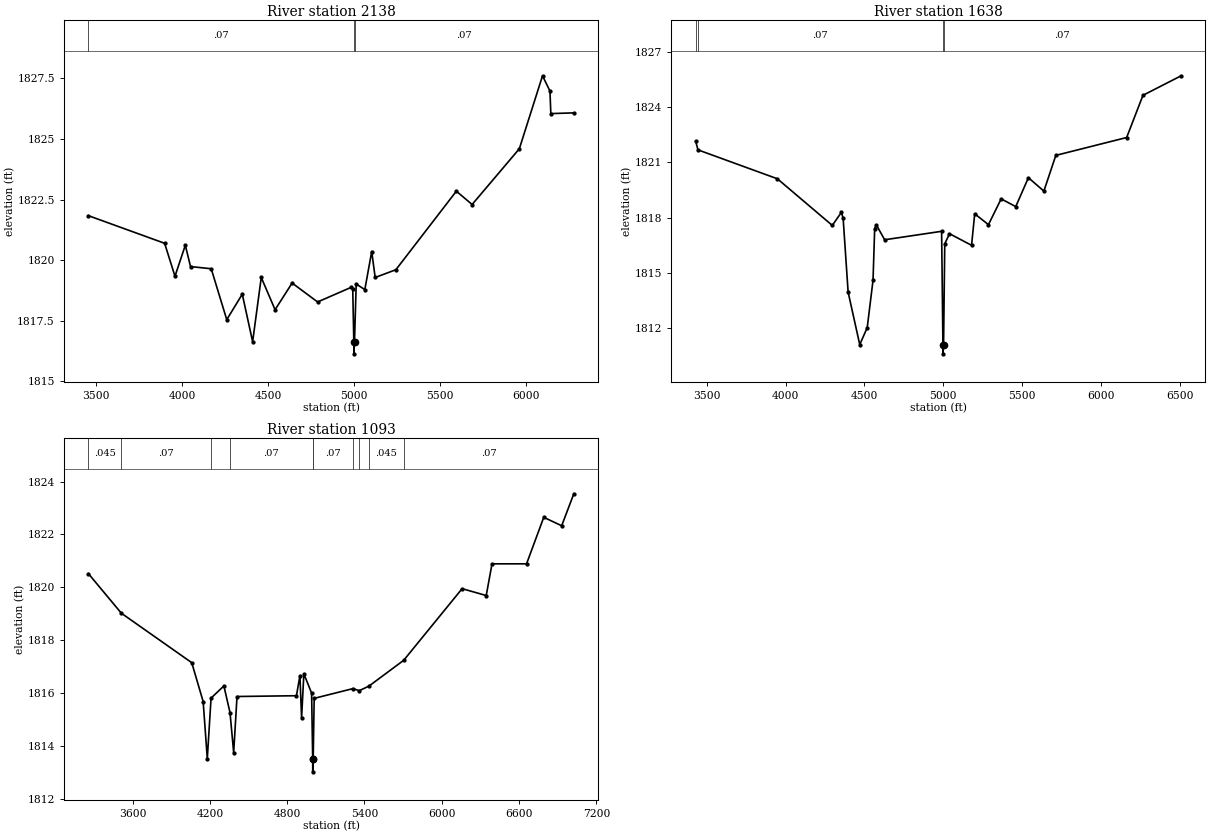
Type RM Length L Ch R = 1,2138,500,500,500
BEGIN DESCRIPTION:
Elm 02 62 3.0
END DESCRIPTION:
XS GIS Cut Line= 4
      1561113.24      6815880.36      1562442.70      6815961.89
      1563192.29      6815915.69      1563909.16      6815753.31
#Sta/Elev= 30
  3457.1 1821.84  3899.7 1820.70  3959.8 1819.34  4019.9 1820.62  4050.0 1819.74
  4170.2 1819.65  4260.4 1817.55  4350.5 1818.60  4410.6 1816.64  4460.7 1819.29
  4540.9 1817.96  4639.9 1819.06  4787.7 1818.28  4981.7 1818.88  4991.7 1818.83
  4998.0 1816.64  4998.3 1816.14  5002.0 1816.64  5011.8 1819.02  5061.9 1818.79
  5101.9 1820.36  5122.0 1819.29  5242.2 1819.61  5593.3 1822.85  5684.7 1822.30
  5958.9 1824.60  6093.4 1827.61  6136.6 1826.98  6141.7 1826.05  6275.1 1826.08
#Mann=3,-1,0
  3457.1    0.07       0  4998.0    0.07       0  5002.0    0.07       0
Bank Sta=4998,5002
Exp/Cntr=0.3,0.1

Type RM Length L Ch R = 1,1638,545,545,545
BEGIN DESCRIPTION:
Elm 02 62 2.0
END DESCRIPTION:
XS GIS Cut Line= 4
      1561056.59      6815930.18      1562411.46      6816379.65
      1562760.36      6816369.15      1563950.41      6815833.21
#Sta/Elev= 30
  3428.5 1822.15  3442.6 1821.68  3947.0 1820.11  4295.5 1817.58  4353.6 1818.29
  4364.5 1817.96  4396.1 1813.96  4469.9 1811.11  4517.3 1812.03  4554.2 1814.60
  4564.7 1817.41  4575.2 1817.61  4627.9 1816.80  4989.6 1817.26  4998.0 1811.11
  4998.3 1810.61  5002.0 1811.11  5009.6 1816.58  5039.6 1817.13  5179.7 1816.50
  5199.7 1818.21  5286.9 1817.62  5367.6 1819.02  5460.2 1818.60  5540.6 1820.17
  5638.7 1819.44  5714.6 1821.38  6164.3 1822.35  6267.8 1824.64  6510.2 1825.70
#Mann=4,-1,0
  3428.5   0.045       0  3442.6    0.07       0  4998.0    0.07       0
  5002.0    0.07       0
Bank Sta=4998,5002
Exp/Cntr=0.3,0.1

Type RM Length L Ch R = 1,1093,0,0,0
BEGIN DESCRIPTION:
Elm 02 62 1.0
END DESCRIPTION:
XS GIS Cut Line= 4
      1560890.50      6816392.60      1562464.79      6816894.55
      1562751.11      6816878.69      1564380.85      6816048.60
#Sta/Elev= 30
  3256.8 1820.52  3513.1 1819.02  4059.2 1817.15  4147.7 1815.68  4179.9 1813.52
  4209.1 1815.81  4308.7 1816.27  4356.2 1815.26  4384.6 1813.75  4410.6 1815.87
  4871.9 1815.90  4898.9 1816.66  4911.8 1815.06  4929.4 1816.73  4989.5 1816.00
  4998.0 1813.52  4998.3 1813.02  5002.0 1813.52  5009.5 1815.80  5311.4 1816.17
  5358.4 1816.09  5433.6 1816.26  5704.4 1817.24  6157.9 1819.95  6345.0 1819.69
  6389.9 1820.89  6658.1 1820.89  6791.6 1822.65  6930.6 1822.33  7024.9 1823.54
#Mann=10,-1,0
  3256.8   0.045       0  3513.1    0.07       0  4209.1    0.16       0
  4356.2    0.07       0  4998.0    0.07       0  5002.0    0.07       0
  5311.4   0.045       0  5358.4    0.07       0  5433.6   0.045       0
  5704.4    0.07       0
Bank Sta=4998,5002
Exp/Cntr=0.3,0.1

Chan Stop Cuts=-1