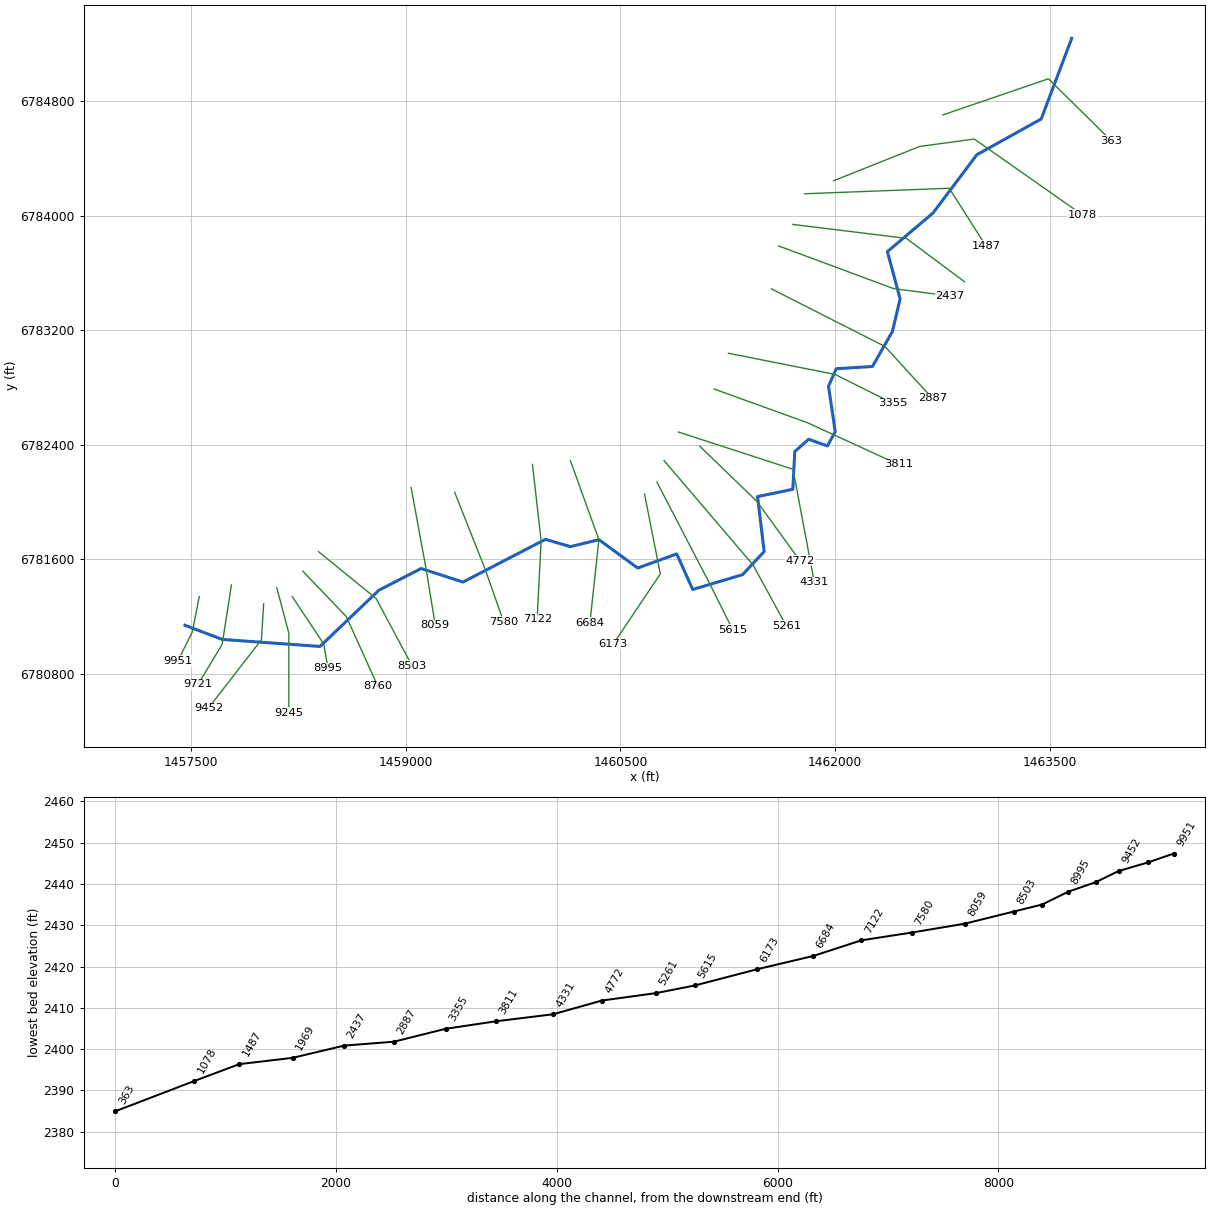
--- Elm 03.prj (project) ---

Proj Title=Elm 03 Base Level Engineering
Current Plan=p01
Default Exp/Contr=0.3,0.1
English Units
Geom File=g01
Flow File=f01
Plan File=p01
BEGIN DESCRIPTION:
Elm 03
END DESCRIPTION:

--- Elm 03.p01 (plan) ---

Plan Title=Multiple Run
Short Identifier=Multiple
Geom File=g01
Flow File=f01
Subcritical Flow
K Sum by GR= 0
Std Step Tol= 0.01
Critical Tol= 0.01
Num of Std Step Trials= 20
Max Error Tol= 0.3
Flow Tol Ratio= 0.001
Split Flow NTrial= 30
Split Flow Tol= 0.02
Split Flow Ratio= 0.02
Log Output Level= 0
Friction Slope Method= 1
Unsteady Friction Slope Method= 2
Unsteady Bridges Friction Slope Method= 1
Parabolic Critical Depth
Global Vel Dist=  1 , 1 , 1
Global Log Level= 0
CheckData=True
Encroach Param= -1, 0, 0, 0
BEGIN DESCRIPTION:
Multiple Run
END DESCRIPTION:

--- Elm 03.f01 (steady flow) ---

Flow Title=Multiple
Number of Profiles=7
Profile Names=10-year,25-year,50-year,1pct_min,100-year,1pct_plu,500-year
River Rch & RM= Elm 03,Reach-1,9951
     213     290     353     265     425     585     625
River Rch & RM= Elm 03,Reach-1,9245
     287     399     491     374     600     825     905
River Rch & RM= Elm 03,Reach-1,5615
     375     530     660     507     813    1120    1250
River Rch & RM= Elm 03,Reach-1,4331
     490     701     879     682    1090    1500    1710
Boundary for River Rch & Prof#=Elm 03,Reach-1,1
Up Type=0
Dn Type=3
Dn Slope=0.005
Boundary for River Rch & Prof#=Elm 03,Reach-1,2
Up Type=0
Dn Type=3
Dn Slope=0.005
Boundary for River Rch & Prof#=Elm 03,Reach-1,3
Up Type=0
Dn Type=3
Dn Slope=0.005
Boundary for River Rch & Prof#=Elm 03,Reach-1,4
Up Type=0
Dn Type=3
Dn Slope=0.005
Boundary for River Rch & Prof#=Elm 03,Reach-1,5
Up Type=0
Dn Type=3
Dn Slope=0.005
Boundary for River Rch & Prof#=Elm 03,Reach-1,6
Up Type=0
Dn Type=3
Dn Slope=0.005
Boundary for River Rch & Prof#=Elm 03,Reach-1,7
Up Type=0
Dn Type=3
Dn Slope=0.005

--- Elm 03.g01 (geometry) ---

Geom Title=Existing Conditions

River Reach=Elm 03,Reach-1
Reach XY= 30
      1457455.00      6781138.00      1457715.50      6781039.22
      1458399.15      6780990.06      1458810.47      6781382.74
      1459106.47      6781534.46      1459398.88      6781439.76
      1459975.05      6781738.21      1460149.97      6781687.19
      1460349.03      6781735.86      1460620.36      6781537.89
      1460893.19      6781636.40      1461005.00      6781388.00
      1461353.54      6781491.54      1461504.62      6781653.16
      1461458.36      6782036.75      1461705.00      6782088.00
      1461718.63      6782351.37      1461815.61      6782437.40
      1461946.54      6782390.62      1462001.27      6782489.52
      1461954.60      6782808.15      1462008.35      6782929.91
      1462261.48      6782945.69      1462401.17      6783189.58
      1462455.11      6783417.91      1462366.23      6783748.02
      1462685.22      6784017.91      1462991.44      6784424.51
      1463441.60      6784674.69      1463655.00      6785238.00

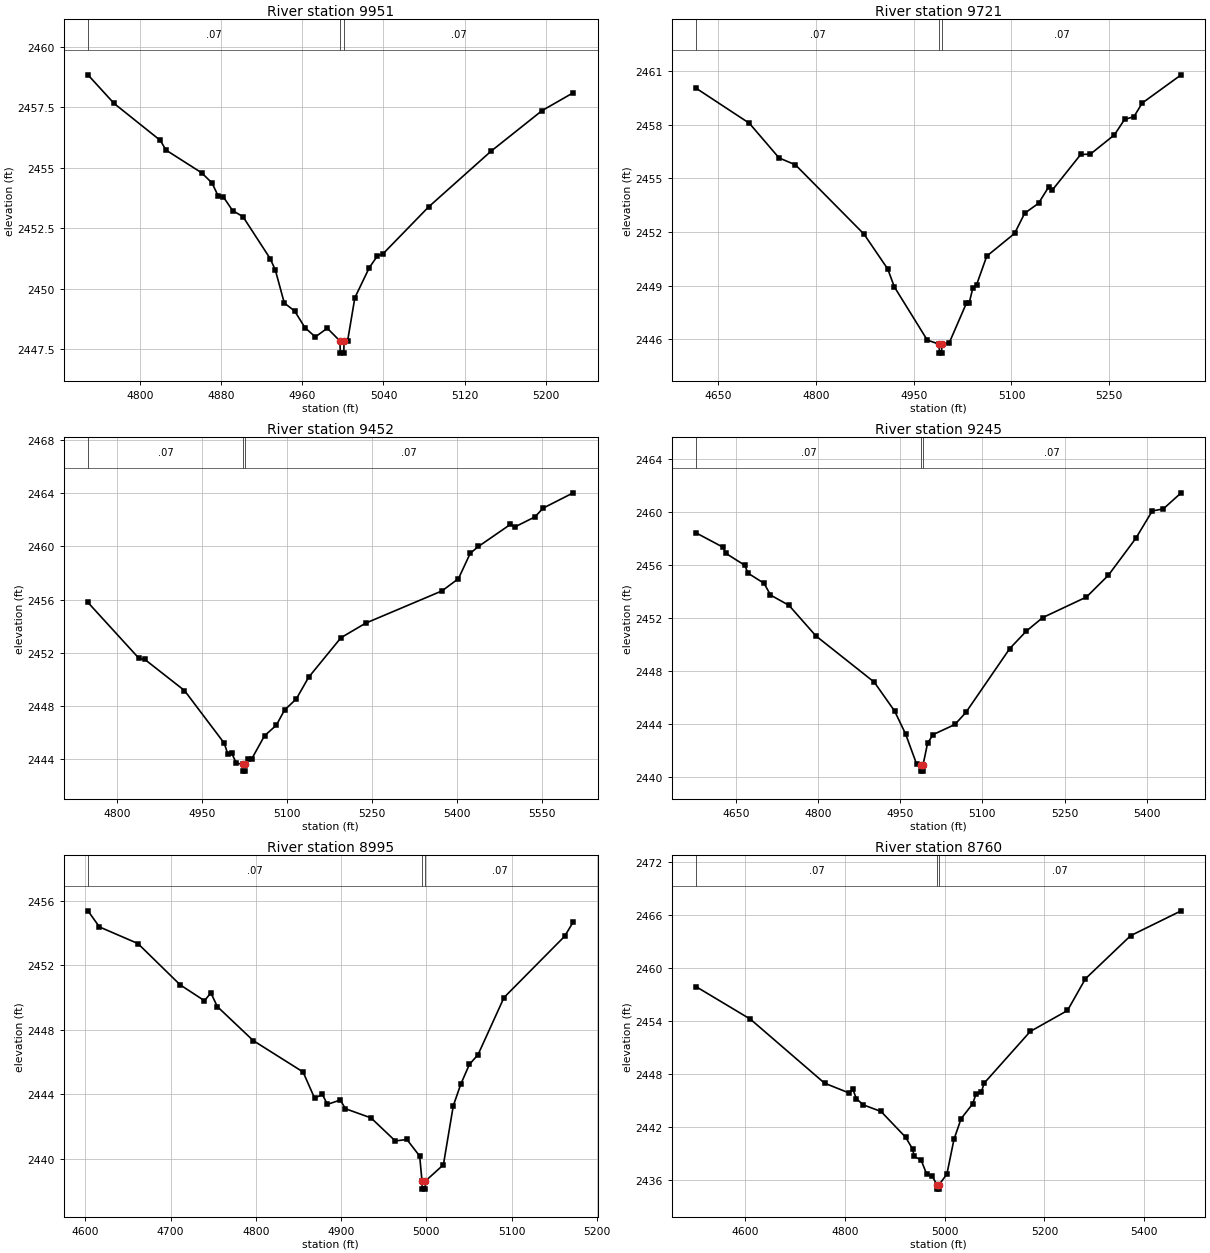
Type RM Length L Ch R = 1,9951,230,230,230
BEGIN DESCRIPTION:
elmc84
END DESCRIPTION:
XS GIS Cut Line= 3
      1457555.01      6781338.05      1457506.37      6781091.30
      1457404.99      6780887.97
#Sta/Elev= 30
  4748.5 2458.84  4774.2 2457.66  4819.9 2456.13  4825.5 2455.73  4860.7 2454.79
  4870.9 2454.37  4876.9 2453.84  4882.0 2453.80  4891.2 2453.23  4901.4 2452.98
  4928.2 2451.25  4933.3 2450.78  4942.2 2449.41  4952.4 2449.08  4962.6 2448.39
  4972.8 2448.01  4984.6 2448.37  4997.1 2447.84  4997.4 2447.34  5000.9 2447.34
  5001.1 2447.84  5004.6 2447.84  5011.8 2449.63  5026.0 2450.87  5034.1 2451.36
  5039.7 2451.45  5084.5 2453.38  5146.0 2455.68  5196.4 2457.36  5227.2 2458.10
#Mann=3,-1,0
  4748.5    0.07       0  4997.1    0.07       0  5001.1    0.07       0
Bank Sta=4997.1,5001.1
Exp/Cntr=0.3,0.1

Type RM Length L Ch R = 1,9721,269,269,269
BEGIN DESCRIPTION:
elmc236
END DESCRIPTION:
XS GIS Cut Line= 3
      1457779.72      6781419.08      1457714.95      6781004.58
      1457546.55      6780726.06
#Sta/Elev= 30
  4615.5 2460.06  4697.6 2458.09  4743.2 2456.15  4768.4 2455.76  4873.7 2451.88
  4910.1 2449.93  4920.2 2448.93  4970.8 2445.95  4989.1 2445.72  4989.3 2445.22
  4992.8 2445.22  4993.1 2445.72  5004.3 2445.78  5030.8 2448.01  5035.0 2448.01
  5040.7 2448.86  5046.6 2449.06  5062.1 2450.65  5104.8 2451.92  5120.3 2453.05
  5141.6 2453.61  5157.1 2454.52  5163.0 2454.36  5206.3 2456.34  5221.2 2456.36
  5258.1 2457.44  5273.6 2458.30  5288.1 2458.46  5300.7 2459.22  5360.5 2460.80
#Mann=3,-1,0
  4615.5    0.07       0  4989.1    0.07       0  4993.1    0.07       0
Bank Sta=4989.1,4993.1
Exp/Cntr=0.3,0.1

Type RM Length L Ch R = 1,9452,207,207,207
BEGIN DESCRIPTION:
elmc83
END DESCRIPTION:
XS GIS Cut Line= 3
      1458005.00      6781288.02      1457989.78      6781037.48
      1457618.91      6780559.11
#Sta/Elev= 30
  4749.0 2455.79  4839.2 2451.58  4849.2 2451.51  4919.3 2449.17  4989.5 2445.21
  4995.5 2444.43  5002.8 2444.44  5010.8 2443.72  5022.6 2443.61  5022.9 2443.11
  5026.4 2443.11  5026.6 2443.61  5031.6 2444.05  5038.0 2444.03  5060.6 2445.77
  5081.4 2446.56  5095.9 2447.70  5116.7 2448.54  5138.5 2450.17  5195.5 2453.14
  5238.9 2454.23  5373.8 2456.66  5402.8 2457.58  5423.6 2459.49  5438.1 2460.00
  5494.2 2461.65  5502.4 2461.47  5537.7 2462.22  5552.2 2462.88  5605.3 2464.03
#Mann=3,-1,0
  4749.0    0.07       0  5022.6    0.07       0  5026.6    0.07       0
Bank Sta=5022.6,5026.6
Exp/Cntr=0.3,0.1

Type RM Length L Ch R = 1,9245,250,250,250
BEGIN DESCRIPTION:
elmc235
END DESCRIPTION:
XS GIS Cut Line= 3
      1458097.07      6781399.69      1458181.28      6781082.30
      1458181.28      6780525.27
#Sta/Elev= 30
  4577.2 2458.45  4626.6 2457.36  4631.7 2456.90  4666.8 2455.98  4672.1 2455.40
  4701.8 2454.62  4713.4 2453.74  4747.1 2452.96  4796.2 2450.65  4902.7 2447.15
  4939.9 2444.96  4959.9 2443.23  4979.9 2440.96  4987.9 2440.92  4988.1 2440.42
  4991.6 2440.42  4991.9 2440.92  4999.9 2442.52  5009.9 2443.18  5049.9 2443.95
  5069.9 2444.86  5149.9 2449.69  5179.9 2451.00  5209.9 2452.03  5289.9 2453.59
  5329.9 2455.24  5379.9 2458.03  5409.9 2460.10  5429.9 2460.25  5462.6 2461.47
#Mann=3,-1,0
  4577.2    0.07       0  4987.9    0.07       0  4991.9    0.07       0
Bank Sta=4987.9,4991.9
Exp/Cntr=0.3,0.1

Type RM Length L Ch R = 1,8995,235,235,235
BEGIN DESCRIPTION:
elmc82
END DESCRIPTION:
XS GIS Cut Line= 3
      1458205.02      6781337.98      1458425.16      6781007.61
      1458455.00      6780838.01
#Sta/Elev= 30
  4603.0 2455.37  4616.5 2454.37  4661.6 2453.34  4711.1 2450.78  4739.7 2449.79
  4747.2 2450.28  4754.7 2449.43  4796.8 2447.32  4855.3 2445.37  4868.9 2443.74
  4877.9 2443.98  4883.9 2443.36  4899.0 2443.63  4905.0 2443.09  4935.0 2442.52
  4963.5 2441.09  4977.1 2441.18  4992.1 2440.15  4994.8 2438.60  4995.0 2438.10
  4998.5 2438.10  4998.8 2438.60  5019.9 2439.61  5031.5 2443.27  5040.2 2444.60
  5050.4 2445.84  5060.5 2446.44  5091.0 2449.99  5162.1 2453.79  5172.2 2454.68
#Mann=3,-1,0
  4603.0    0.07       0  4994.8    0.07       0  4998.8    0.07       0
Bank Sta=4994.8,4998.8
Exp/Cntr=0.3,0.1

Type RM Length L Ch R = 1,8760,257,257,257
BEGIN DESCRIPTION:
elmc234
END DESCRIPTION:
XS GIS Cut Line= 3
      1458278.40      6781516.27      1458582.83      6781198.88
      1458803.03      6780713.15
#Sta/Elev= 30
  4501.0 2457.90  4610.4 2454.21  4759.1 2446.98  4808.5 2445.87  4815.8 2446.32
  4822.7 2445.23  4836.8 2444.53  4872.4 2443.78  4921.7 2440.87  4935.9 2439.51
  4938.7 2438.70  4952.7 2438.30  4963.7 2436.72  4974.7 2436.47  4984.7 2435.51
  4985.0 2435.01  4988.6 2435.01  4988.8 2435.51  5004.4 2436.71  5018.6 2440.63
  5032.9 2442.97  5056.0 2444.64  5062.5 2445.71  5073.5 2445.99  5079.1 2446.98
  5171.5 2452.82  5246.2 2455.19  5282.1 2458.77  5372.7 2463.64  5474.1 2466.45
#Mann=3,-1,0
  4501.0    0.07       0  4984.7    0.07       0  4988.8    0.07       0
Bank Sta=4984.7,4988.8
Exp/Cntr=0.3,0.1

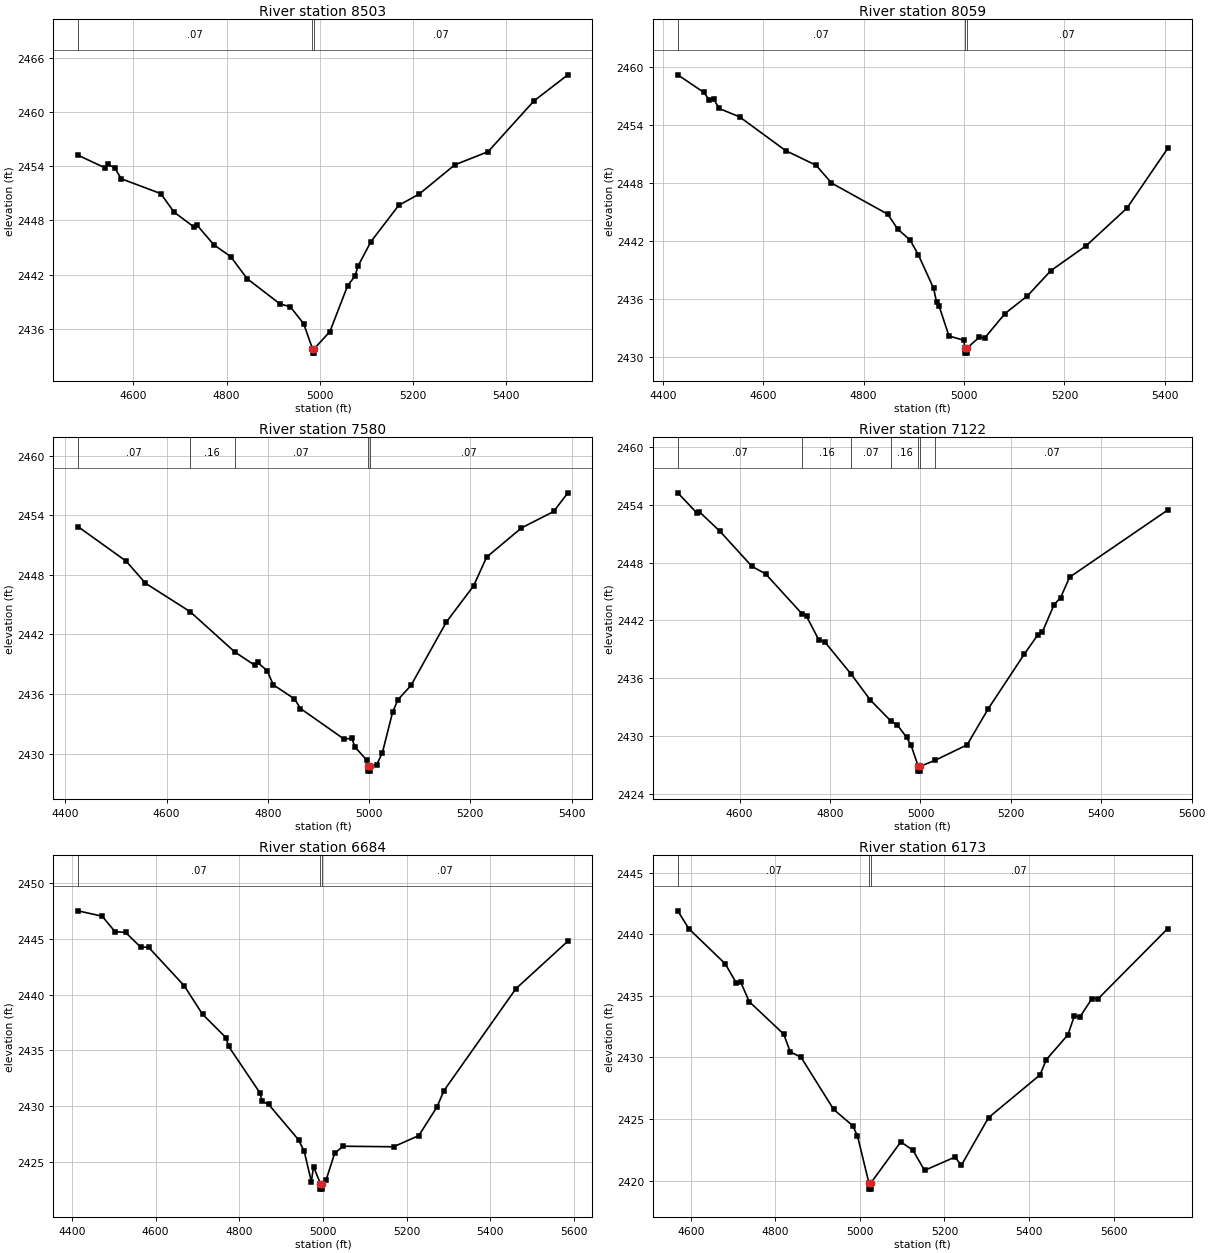
Type RM Length L Ch R = 1,8503,444,444,444
BEGIN DESCRIPTION:
elmc81
END DESCRIPTION:
XS GIS Cut Line= 3
      1458388.53      6781652.25      1458791.26      6781325.05
      1459042.67      6780855.63
#Sta/Elev= 30
  4481.1 2455.21  4538.9 2453.82  4545.4 2454.19  4559.8 2453.83  4574.1 2452.60
  4658.9 2450.96  4687.6 2448.90  4730.7 2447.25  4737.2 2447.44  4772.9 2445.29
  4809.0 2443.99  4844.2 2441.55  4914.6 2438.76  4936.9 2438.44  4965.6 2436.56
  4984.4 2433.81  4984.6 2433.31  4988.2 2433.31  4988.5 2433.81  5021.8 2435.69
  5060.0 2440.78  5076.1 2441.86  5081.9 2442.92  5110.1 2445.66  5169.6 2449.66
  5213.5 2450.91  5289.9 2454.14  5361.4 2455.60  5459.7 2461.21  5532.5 2464.10
#Mann=3,-1,0
  4481.1    0.07       0  4984.4    0.07       0  4988.5    0.07       0
Bank Sta=4984.4,4988.5
Exp/Cntr=0.3,0.1

Type RM Length L Ch R = 1,8059,479,479,479
BEGIN DESCRIPTION:
elmc80
END DESCRIPTION:
XS GIS Cut Line= 3
      1459036.21      6782099.14      1459139.81      6781538.53
      1459205.00      6781138.00
#Sta/Elev= 30
  4429.9 2459.15  4481.9 2457.33  4492.1 2456.59  4501.5 2456.63  4512.4 2455.67
  4553.1 2454.80  4644.6 2451.32  4705.6 2449.79  4736.1 2447.96  4848.0 2444.74
  4868.3 2443.18  4892.4 2442.08  4909.0 2440.55  4939.5 2437.07  4945.3 2435.67
  4950.4 2435.25  4970.0 2432.15  5000.0 2431.69  5001.2 2430.87  5001.5 2430.37
  5005.3 2430.37  5005.6 2430.87  5030.9 2432.03  5041.1 2431.92  5081.6 2434.46
  5126.4 2436.29  5172.8 2438.89  5243.7 2441.49  5324.7 2445.37  5405.8 2451.54
#Mann=3,-1,0
  4429.9    0.07       0  5001.2    0.07       0  5005.6    0.07       0
Bank Sta=5001.2,5005.6
Exp/Cntr=0.3,0.1

Type RM Length L Ch R = 1,7580,458,458,458
BEGIN DESCRIPTION:
elmc79
END DESCRIPTION:
XS GIS Cut Line= 3
      1459340.61      6782066.76      1459552.80      6781531.92
      1459683.34      6781161.55
#Sta/Elev= 30
  4424.6 2452.87  4520.1 2449.38  4558.1 2447.16  4646.2 2444.30  4734.2 2440.25
  4774.2 2438.89  4779.6 2439.18  4798.5 2438.35  4810.6 2436.93  4852.5 2435.51
  4864.4 2434.54  4950.4 2431.46  4965.9 2431.54  4971.9 2430.67  4995.6 2429.32
  4997.2 2428.73  4997.5 2428.23  5001.4 2428.23  5001.7 2428.73  5014.8 2428.86
  5026.2 2430.08  5046.5 2434.19  5057.2 2435.44  5082.7 2436.86  5152.6 2443.25
  5206.5 2446.90  5232.2 2449.79  5301.0 2452.73  5364.7 2454.39  5392.7 2456.27
#Mann=5,-1,0
  4424.6    0.07       0  4646.2    0.16       0  4734.2    0.07       0
  4997.2    0.07       0  5001.7    0.07       0
Bank Sta=4997.2,5001.7
Exp/Cntr=0.3,0.1

Type RM Length L Ch R = 1,7122,438,438,438
BEGIN DESCRIPTION:
elmc78
END DESCRIPTION:
XS GIS Cut Line= 3
      1459884.66      6782261.02      1459945.22      6781727.54
      1459917.14      6781181.26
#Sta/Elev= 30
  4463.1 2455.25  4505.9 2453.13  4510.9 2453.28  4556.7 2451.24  4627.2 2447.61
  4657.4 2446.83  4737.4 2442.71  4747.9 2442.43  4774.7 2440.01  4788.2 2439.77
  4847.1 2436.39  4888.8 2433.74  4934.0 2431.57  4948.9 2431.13  4969.3 2429.85
  4979.4 2429.01  4995.0 2426.84  4995.3 2426.34  4999.2 2426.34  4999.6 2426.84
  5032.2 2427.46  5103.2 2429.07  5149.7 2432.80  5229.8 2438.50  5259.9 2440.51
  5269.9 2440.82  5295.7 2443.64  5310.0 2444.36  5330.0 2446.49  5547.0 2453.46
#Mann=7,-1,0
  4463.1    0.07       0  4737.4    0.16       0  4847.1    0.07       0
  4934.0    0.16       0  4995.0    0.07       0  4999.6    0.16       0
  5032.2    0.07       0
Bank Sta=4995,4999.6
Exp/Cntr=0.3,0.1

Type RM Length L Ch R = 1,6684,511,511,511
BEGIN DESCRIPTION:
elmc77
END DESCRIPTION:
XS GIS Cut Line= 3
      1460150.20      6782286.99      1460349.03      6781735.86
      1460286.21      6781153.54
#Sta/Elev= 30
  4414.1 2447.51  4472.0 2447.03  4502.6 2445.65  4528.0 2445.57  4564.0 2444.26
  4583.1 2444.24  4668.2 2440.79  4712.1 2438.23  4768.1 2436.13  4774.5 2435.35
  4848.9 2431.20  4854.9 2430.42  4870.2 2430.14  4941.6 2426.97  4955.2 2425.94
  4972.3 2423.22  4977.6 2424.55  4993.9 2423.04  4994.2 2422.54  4998.2 2422.54
  4998.6 2423.04  5007.9 2423.39  5028.0 2425.75  5048.1 2426.39  5168.8 2426.34
  5229.2 2427.34  5272.6 2429.90  5289.5 2431.38  5461.4 2440.52  5585.7 2444.79
#Mann=3,-1,0
  4414.1    0.07       0  4993.9    0.07       0  4998.6    0.07       0
Bank Sta=4993.9,4998.6
Exp/Cntr=0.3,0.1

Type RM Length L Ch R = 1,6173,558,558,558
BEGIN DESCRIPTION:
elmc76
END DESCRIPTION:
XS GIS Cut Line= 3
      1460668.34      6782053.82      1460778.45      6781496.81
      1460449.07      6781005.97
#Sta/Elev= 30
  4569.2 2441.90  4595.5 2440.44  4681.5 2437.60  4707.7 2436.04  4717.8 2436.13
  4738.2 2434.53  4819.8 2431.89  4835.3 2430.45  4860.6 2430.02  4937.9 2425.78
  4982.9 2424.46  4994.2 2423.64  5021.3 2419.81  5021.6 2419.31  5025.7 2419.31
  5026.0 2419.81  5096.8 2423.15  5125.6 2422.46  5152.9 2420.83  5224.9 2421.91
  5239.9 2421.24  5304.2 2425.11  5426.0 2428.58  5441.0 2429.82  5492.0 2431.84
  5507.0 2433.33  5520.9 2433.31  5549.0 2434.78  5564.0 2434.78  5728.1 2440.46
#Mann=3,-1,0
  4569.2    0.07       0  5021.3    0.07       0  5026.0    0.07       0
Bank Sta=5021.3,5026
Exp/Cntr=0.3,0.1

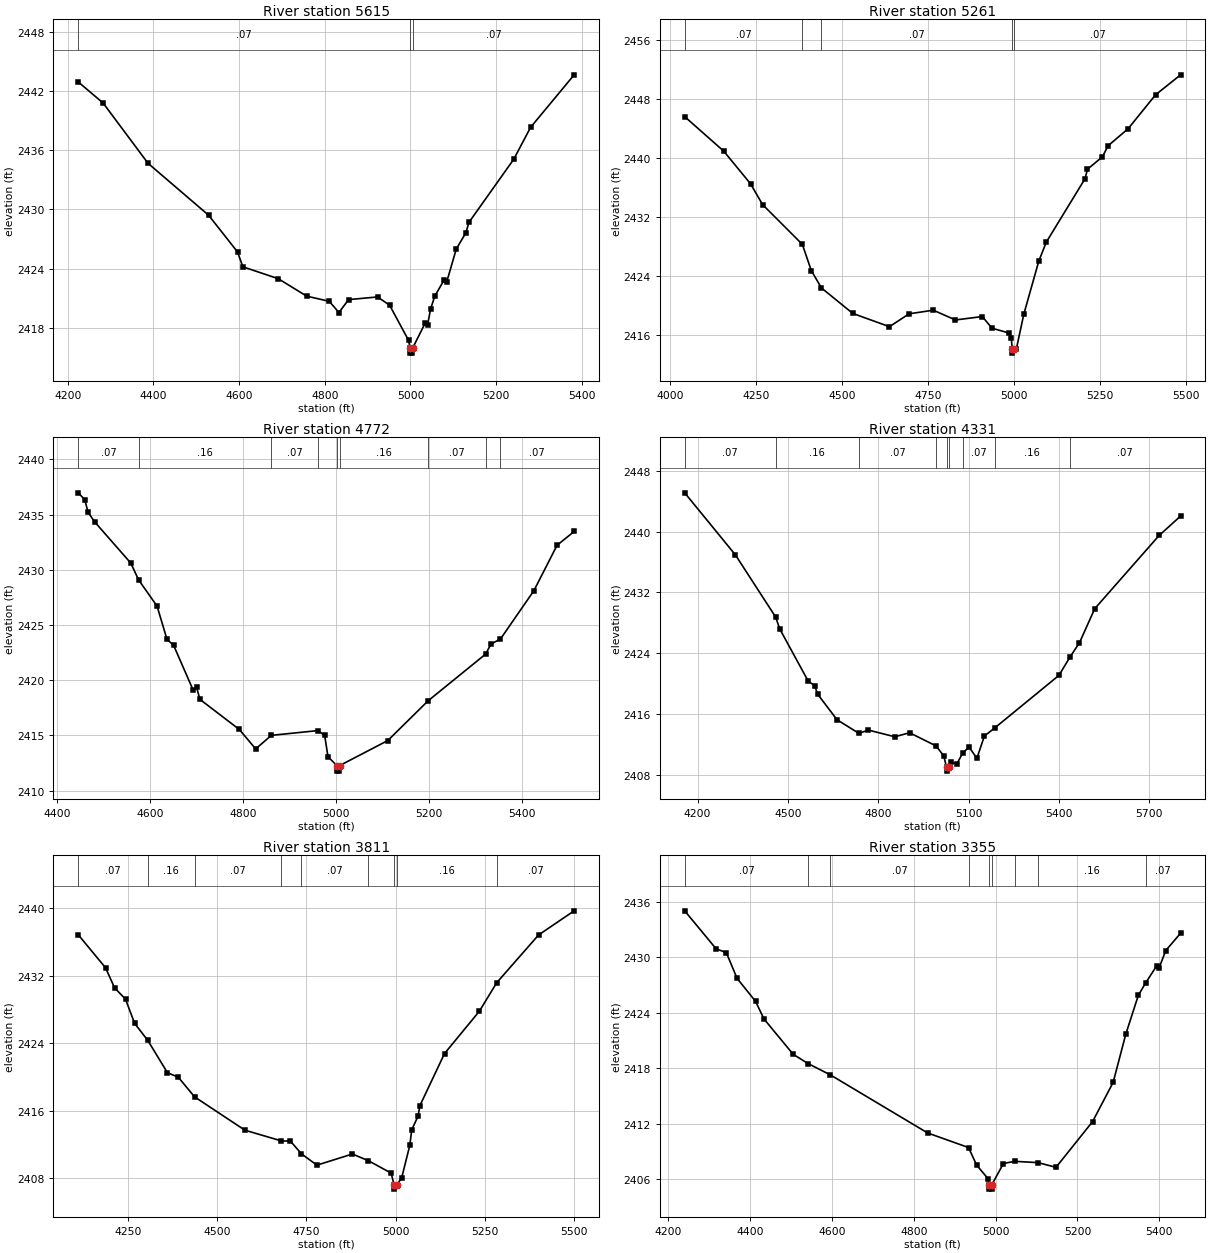
Type RM Length L Ch R = 1,5615,354,354,354
BEGIN DESCRIPTION:
elmc75
END DESCRIPTION:
XS GIS Cut Line= 3
      1460755.02      6782137.96      1461121.71      6781432.04
      1461283.62      6781108.24
#Sta/Elev= 30
  4224.5 2442.94  4282.6 2440.80  4387.5 2434.68  4528.7 2429.42  4596.3 2425.69
  4608.7 2424.18  4691.5 2422.97  4757.8 2421.20  4810.4 2420.68  4833.0 2419.54
  4855.5 2420.85  4923.1 2421.12  4951.2 2420.29  4995.5 2416.72  4999.1 2415.92
  4999.5 2415.42  5004.4 2415.42  5004.9 2415.92  5034.3 2418.47  5039.9 2418.27
  5046.9 2419.90  5056.7 2421.20  5079.0 2422.88  5084.6 2422.65  5107.0 2426.00
  5129.3 2427.63  5136.3 2428.68  5241.1 2435.10  5280.3 2438.33  5382.0 2443.66
#Mann=3,-1,0
  4224.5    0.07       0  4999.1    0.07       0  5004.9    0.07       0
Bank Sta=4999.1,5004.9
Exp/Cntr=0.3,0.1

Type RM Length L Ch R = 1,5261,489,489,489
BEGIN DESCRIPTION:
elmc74
END DESCRIPTION:
XS GIS Cut Line= 3
      1460805.01      6782287.99      1461427.00      6781559.36
      1461659.30      6781134.07
#Sta/Elev= 30
  4042.0 2445.57  4155.6 2440.90  4233.6 2436.48  4268.7 2433.66  4384.3 2428.28
  4410.3 2424.73  4439.9 2422.38  4531.1 2418.93  4637.6 2417.14  4694.7 2418.88
  4765.1 2419.37  4829.7 2418.05  4907.7 2418.51  4936.1 2416.93  4985.6 2416.28
  4992.2 2415.60  4994.7 2414.06  4995.2 2413.56  5000.5 2414.06  5006.8 2414.13
  5028.6 2418.85  5072.2 2426.04  5094.1 2428.60  5206.7 2437.18  5213.6 2438.45
  5257.3 2440.14  5273.4 2441.62  5332.0 2443.94  5411.8 2448.53  5484.6 2451.23
#Mann=5,-1,0
  4042.0    0.07       0  4384.3    0.16       0  4439.9    0.07       0
  4994.7    0.07       0  5000.5    0.07       0
Bank Sta=4994.7,5000.5
Exp/Cntr=0.3,0.1

Type RM Length L Ch R = 1,4772,441,441,441
BEGIN DESCRIPTION:
elmc73
END DESCRIPTION:
XS GIS Cut Line= 3
      1461055.00      6782388.00      1461454.20      6782003.15
      1461755.02      6781587.97
#Sta/Elev= 30
  4445.5 2436.97  4459.5 2436.36  4466.7 2435.21  4480.9 2434.34  4558.6 2430.61
  4575.4 2429.09  4615.2 2426.71  4636.5 2423.70  4650.7 2423.17  4693.1 2419.08
  4700.1 2419.39  4707.3 2418.27  4792.2 2415.54  4827.4 2413.78  4861.1 2415.01
  4961.3 2415.44  4975.8 2415.01  4983.0 2413.07  5002.1 2412.27  5002.6 2411.77
  5007.5 2411.77  5008.0 2412.27  5111.7 2414.54  5198.5 2418.14  5322.3 2422.37
  5333.7 2423.28  5354.1 2423.73  5426.2 2428.12  5475.9 2432.22  5512.7 2433.47
#Mann=9,-1,0
  4445.5    0.07       0  4575.4    0.16       0  4861.1    0.07       0
  4961.3    0.16       0  5002.1    0.07       0  5008.0    0.16       0
  5198.5    0.07       0  5322.3    0.16       0  5354.1    0.07       0
Bank Sta=5002.1,5008
Exp/Cntr=0.3,0.1

Type RM Length L Ch R = 1,4331,520,520,520
BEGIN DESCRIPTION:
elmc72
END DESCRIPTION:
XS GIS Cut Line= 3
      1460904.98      6782488.01      1461706.33      6782227.59
      1461855.01      6781437.97
#Sta/Elev= 30
  4157.4 2445.14  4325.7 2436.96  4459.2 2428.77  4472.9 2427.20  4567.5 2420.31
  4588.5 2419.73  4599.3 2418.56  4663.2 2415.22  4735.7 2413.43  4767.3 2413.86
  4854.9 2412.98  4904.0 2413.51  4991.8 2411.77  5017.3 2410.46  5026.6 2408.95
  5027.1 2408.45  5033.6 2408.95  5040.3 2409.68  5060.6 2409.38  5079.8 2410.81
  5101.3 2411.63  5127.3 2410.14  5152.2 2413.08  5186.8 2414.15  5399.8 2421.08
  5436.1 2423.48  5467.7 2425.37  5518.5 2429.87  5732.2 2439.52  5803.5 2442.08
#Mann=9,-1,0
  4157.4    0.07       0  4459.2    0.16       0  4735.7    0.07       0
  4991.8    0.16       0  5026.6    0.07       0  5033.6    0.16       0
  5079.8    0.07       0  5186.8    0.16       0  5436.1    0.07       0
Bank Sta=5026.6,5033.6
Exp/Cntr=0.3,0.1

Type RM Length L Ch R = 1,3811,456,456,456
BEGIN DESCRIPTION:
elmc71
END DESCRIPTION:
XS GIS Cut Line= 3
      1461155.04      6782787.98      1461808.25      6782552.52
      1462441.53      6782261.73
#Sta/Elev= 30
  4109.8 2436.88  4186.5 2432.96  4211.8 2430.59  4242.5 2429.24  4267.9 2426.39
  4305.1 2424.35  4360.0 2420.54  4390.7 2419.99  4436.2 2417.67  4577.5 2413.72
  4680.0 2412.45  4705.0 2412.43  4736.1 2410.92  4779.4 2409.58  4879.0 2410.90
  4923.6 2410.11  4987.6 2408.64  4995.9 2407.24  4996.4 2406.74  5003.0 2407.24
  5016.9 2408.03  5039.9 2411.92  5045.4 2413.77  5062.9 2415.36  5068.4 2416.64
  5137.3 2422.80  5234.8 2427.80  5283.9 2431.20  5401.2 2436.85  5501.0 2439.71
#Mann=9,-1,0
  4109.8    0.07       0  4305.1    0.16       0  4436.2    0.07       0
  4680.0    0.16       0  4736.1    0.07       0  4923.6    0.16       0
  4995.9    0.07       0  5003.0    0.16       0  5283.9    0.07       0
Bank Sta=4995.9,5003
Exp/Cntr=0.3,0.1

Type RM Length L Ch R = 1,3355,468,468,468
BEGIN DESCRIPTION:
elmc70
END DESCRIPTION:
XS GIS Cut Line= 3
      1461255.01      6783038.00      1462000.60      6782890.19
      1462404.97      6782688.01
#Sta/Elev= 30
  4239.9 2435.05  4316.7 2430.94  4341.8 2430.52  4367.9 2427.74  4413.2 2425.25
  4433.6 2423.35  4505.0 2419.52  4541.2 2418.52  4596.3 2417.28  4833.8 2411.00
  4933.7 2409.42  4953.5 2407.52  4982.3 2406.00  4983.8 2405.42  4984.3 2404.92
  4990.5 2404.92  4991.0 2405.42  5018.9 2407.69  5046.1 2407.93  5103.7 2407.79
  5147.5 2407.28  5236.9 2412.23  5287.2 2416.48  5318.0 2421.68  5348.7 2425.90
  5366.5 2427.24  5393.4 2429.08  5399.0 2428.81  5415.8 2430.75  5452.1 2432.63
#Mann=9,-1,0
  4239.9    0.07       0  4541.2    0.16       0  4596.3    0.07       0
  4933.7    0.16       0  4983.8    0.07       0  4991.0    0.16       0
  5046.1    0.07       0  5103.7    0.16       0  5366.5    0.07       0
Bank Sta=4983.8,4991
Exp/Cntr=0.3,0.1

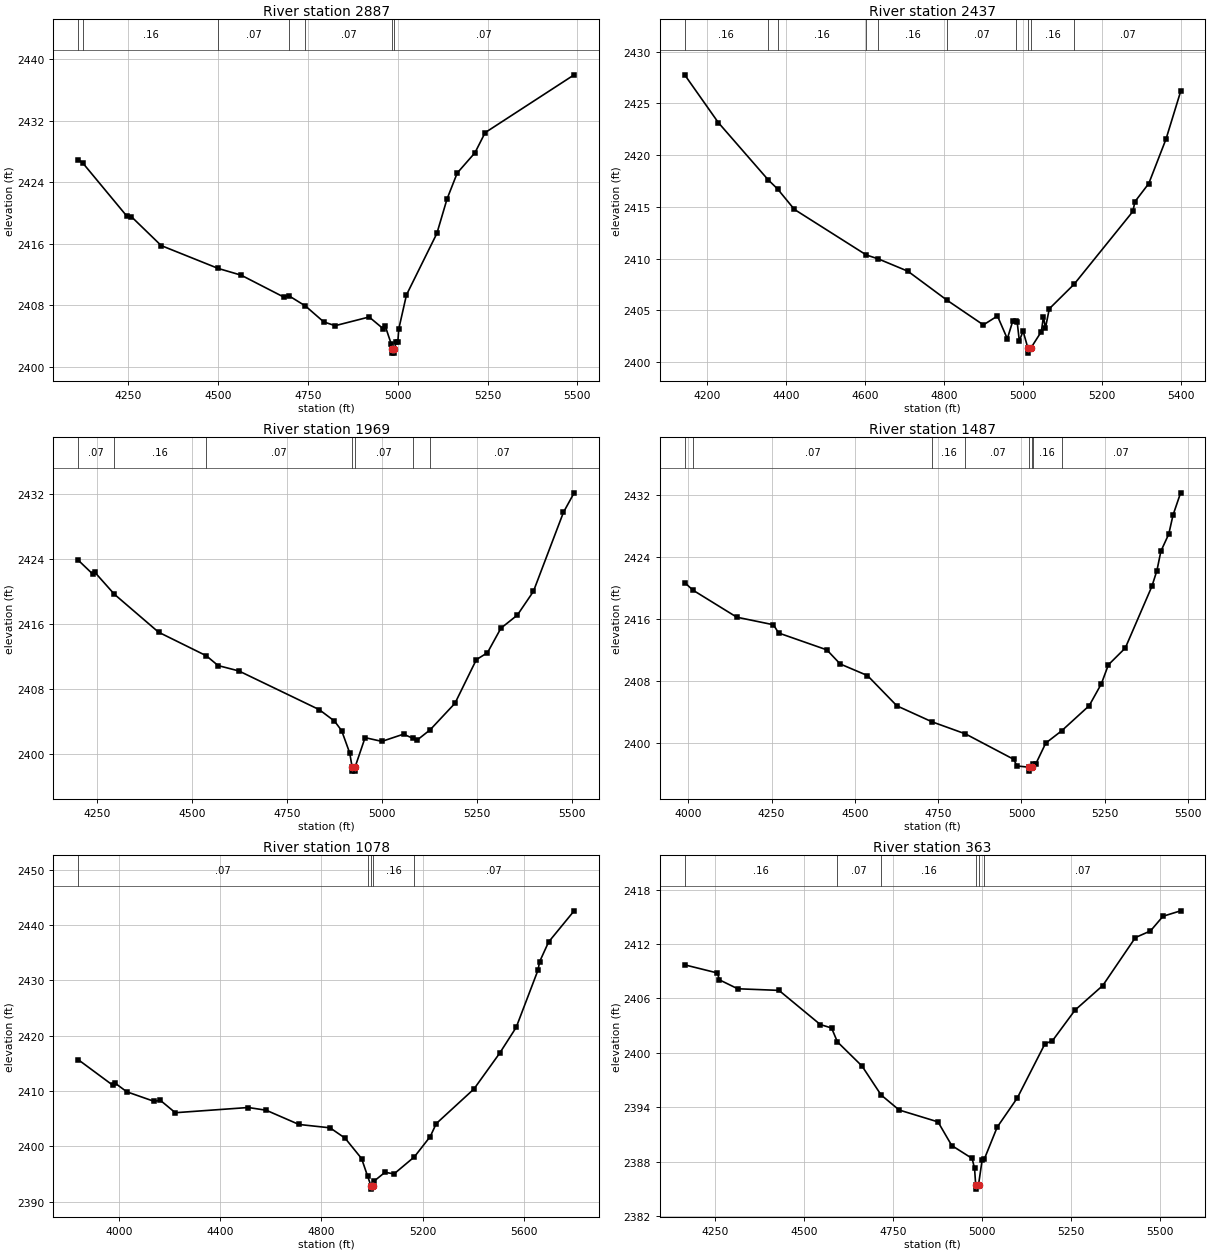
Type RM Length L Ch R = 1,2887,450,450,450
BEGIN DESCRIPTION:
elmc69
END DESCRIPTION:
XS GIS Cut Line= 3
      1461554.99      6783488.01      1462348.92      6783085.80
      1462680.34      6782723.39
#Sta/Elev= 30
  4110.0 2426.98  4123.6 2426.48  4244.5 2419.67  4257.6 2419.57  4341.1 2415.79
  4500.2 2412.81  4563.8 2411.94  4681.7 2409.11  4695.7 2409.29  4742.8 2407.93
  4793.8 2405.86  4825.5 2405.37  4920.2 2406.50  4959.2 2404.98  4964.8 2405.35
  4981.4 2403.03  4983.4 2402.30  4983.9 2401.80  4990.2 2401.80  4990.7 2402.30
  4995.0 2403.21  5000.0 2403.21  5002.7 2404.94  5024.1 2409.37  5108.8 2417.37
  5137.1 2421.85  5165.5 2425.23  5214.8 2427.86  5243.2 2430.48  5491.1 2438.00
#Mann=7,-1,0
  4110.0    0.07       0  4123.6    0.16       0  4500.2    0.07       0
  4695.7    0.16       0  4742.8    0.07       0  4983.4    0.07       0
  4990.7    0.07       0
Bank Sta=4983.4,4990.7
Exp/Cntr=0.3,0.1

Type RM Length L Ch R = 1,2437,468,468,468
BEGIN DESCRIPTION:
elmc68
END DESCRIPTION:
XS GIS Cut Line= 3
      1461605.02      6783787.99      1462409.19      6783489.74
      1462805.02      6783438.00
#Sta/Elev= 30
  4142.3 2427.77  4227.6 2423.15  4353.6 2417.63  4377.6 2416.74  4420.2 2414.76
  4602.7 2410.35  4633.1 2409.97  4708.0 2408.78  4807.8 2405.96  4899.3 2403.59
  4935.0 2404.45  4960.0 2402.25  4974.2 2404.01  4982.7 2403.92  4984.9 2403.90
  4990.4 2402.05  5000.0 2402.99  5012.0 2401.36  5012.5 2400.86  5019.8 2401.36
  5046.2 2402.94  5051.6 2404.39  5056.6 2403.28  5066.4 2405.15  5129.2 2407.52
  5278.2 2414.56  5283.3 2415.50  5318.5 2417.26  5362.2 2421.56  5399.2 2426.16
#Mann=10,-1,0
  4142.3    0.16       0  4353.6    0.07       0  4377.6    0.16       0
  4602.7    0.07       0  4633.1    0.16       0  4807.8    0.07       0
  4982.7    0.16       0  5012.0    0.07       0  5019.8    0.16       0
  5129.2    0.07       0
Bank Sta=5012,5019.8
Exp/Cntr=0.3,0.1

Type RM Length L Ch R = 1,1969,482,482,482
BEGIN DESCRIPTION:
elmc67
END DESCRIPTION:
XS GIS Cut Line= 3
      1461705.01      6783938.00      1462498.95      6783840.53
      1462905.03      6783537.98
#Sta/Elev= 30
  4200.1 2423.85  4238.2 2422.15  4243.3 2422.39  4295.3 2419.66  4411.7 2414.99
  4537.4 2412.09  4568.6 2410.88  4623.2 2410.22  4834.8 2405.46  4875.1 2404.05
  4894.0 2402.87  4915.4 2400.10  4921.5 2398.39  4922.0 2397.89  4928.9 2397.89
  4929.4 2398.39  4955.7 2402.01  5000.0 2401.55  5057.0 2402.44  5082.4 2401.91
  5092.5 2401.70  5127.2 2402.98  5192.5 2406.24  5248.8 2411.61  5278.0 2412.46
  5313.5 2415.48  5356.7 2417.09  5399.0 2420.00  5478.2 2429.74  5506.4 2432.14
#Mann=7,-1,0
  4200.1    0.07       0  4295.3    0.16       0  4537.4    0.07       0
  4921.5    0.07       0  4929.4    0.07       0  5082.4    0.16       0
  5127.2    0.07       0
Bank Sta=4921.5,4929.4
Exp/Cntr=0.3,0.1

Type RM Length L Ch R = 1,1487,409,409,409
BEGIN DESCRIPTION:
elmc66
END DESCRIPTION:
XS GIS Cut Line= 3
      1461788.80      6784152.27      1462798.57      6784190.69
      1463054.99      6783788.01
#Sta/Elev= 30
  3989.5 2420.72  4014.0 2419.75  4145.8 2416.25  4255.9 2415.27  4271.3 2414.21
  4416.0 2412.03  4456.0 2410.21  4537.9 2408.71  4626.2 2404.80  4731.4 2402.74
  4831.8 2401.18  4976.4 2397.90  4986.4 2397.04  5023.1 2396.87  5023.6 2396.37
  5031.1 2396.87  5034.3 2397.29  5042.3 2397.25  5072.8 2399.99  5120.6 2401.58
  5203.1 2404.82  5239.5 2407.64  5260.7 2410.10  5311.4 2412.27  5391.1 2420.22
  5406.3 2422.27  5418.2 2424.77  5441.8 2426.98  5454.6 2429.43  5477.4 2432.31
#Mann=8,-1,0
  3989.5    0.16       0  4014.0    0.07       0  4731.4    0.16       0
  4831.8    0.07       0  5023.1    0.07       0  5031.1    0.07       0
  5034.3    0.16       0  5120.6    0.07       0
Bank Sta=5023.1,5031.1
Exp/Cntr=0.3,0.1

Type RM Length L Ch R = 1,1078,715,715,715
BEGIN DESCRIPTION:
elmc233
END DESCRIPTION:
XS GIS Cut Line= 4
      1461989.63      6784242.96      1462591.93      6784482.58
      1462974.06      6784534.40      1463730.93      6784003.94
#Sta/Elev= 30
  3840.1 2415.66  3977.9 2411.00  3985.8 2411.42  4031.9 2409.86  4139.8 2408.13
  4164.1 2408.33  4223.4 2406.08  4511.6 2407.02  4582.2 2406.53  4711.5 2403.96
  4834.5 2403.35  4893.6 2401.49  4959.0 2397.80  4982.9 2394.59  4996.8 2392.78
  4997.3 2392.28  5004.8 2392.78  5009.4 2393.77  5051.4 2395.32  5087.1 2395.03
  5167.4 2398.11  5230.1 2401.78  5253.6 2404.11  5402.7 2410.37  5503.8 2416.81
  5569.2 2421.48  5655.5 2431.84  5661.6 2433.33  5697.3 2436.91  5798.2 2442.54
#Mann=5,-1,0
  3840.1    0.07       0  4982.9    0.16       0  4996.8    0.07       0
  5004.8    0.16       0  5167.4    0.07       0
Bank Sta=4996.8,5004.8
Exp/Cntr=0.3,0.1

Type RM Length L Ch R = 1,363,0,0,0
BEGIN DESCRIPTION:
elmc65
END DESCRIPTION:
XS GIS Cut Line= 3
      1462753.87      6784702.80      1463492.20      6784955.38
      1463930.54      6784523.49
#Sta/Elev= 30
  4163.3 2409.71  4255.5 2408.81  4260.8 2408.06  4312.5 2407.07  4428.7 2406.89
  4545.0 2403.12  4576.7 2402.74  4593.1 2401.21  4662.4 2398.54  4716.1 2395.35
  4766.9 2393.69  4876.2 2392.38  4914.9 2389.77  4972.1 2388.35  4979.1 2387.26
  4982.2 2385.46  4982.7 2384.96  4990.3 2385.46  5000.4 2388.16  5006.6 2388.28
  5042.8 2391.80  5099.4 2395.02  5177.1 2400.99  5198.4 2401.34  5262.0 2404.72
  5339.8 2407.42  5431.7 2412.72  5474.1 2413.45  5509.4 2415.07  5559.0 2415.67
#Mann=6,-1,0
  4163.3    0.16       0  4593.1    0.07       0  4716.1    0.16       0
  4982.2    0.07       0  4990.3    0.16       0  5006.6    0.07       0
Bank Sta=4982.2,4990.3
Exp/Cntr=0.3,0.1

Chan Stop Cuts=-1