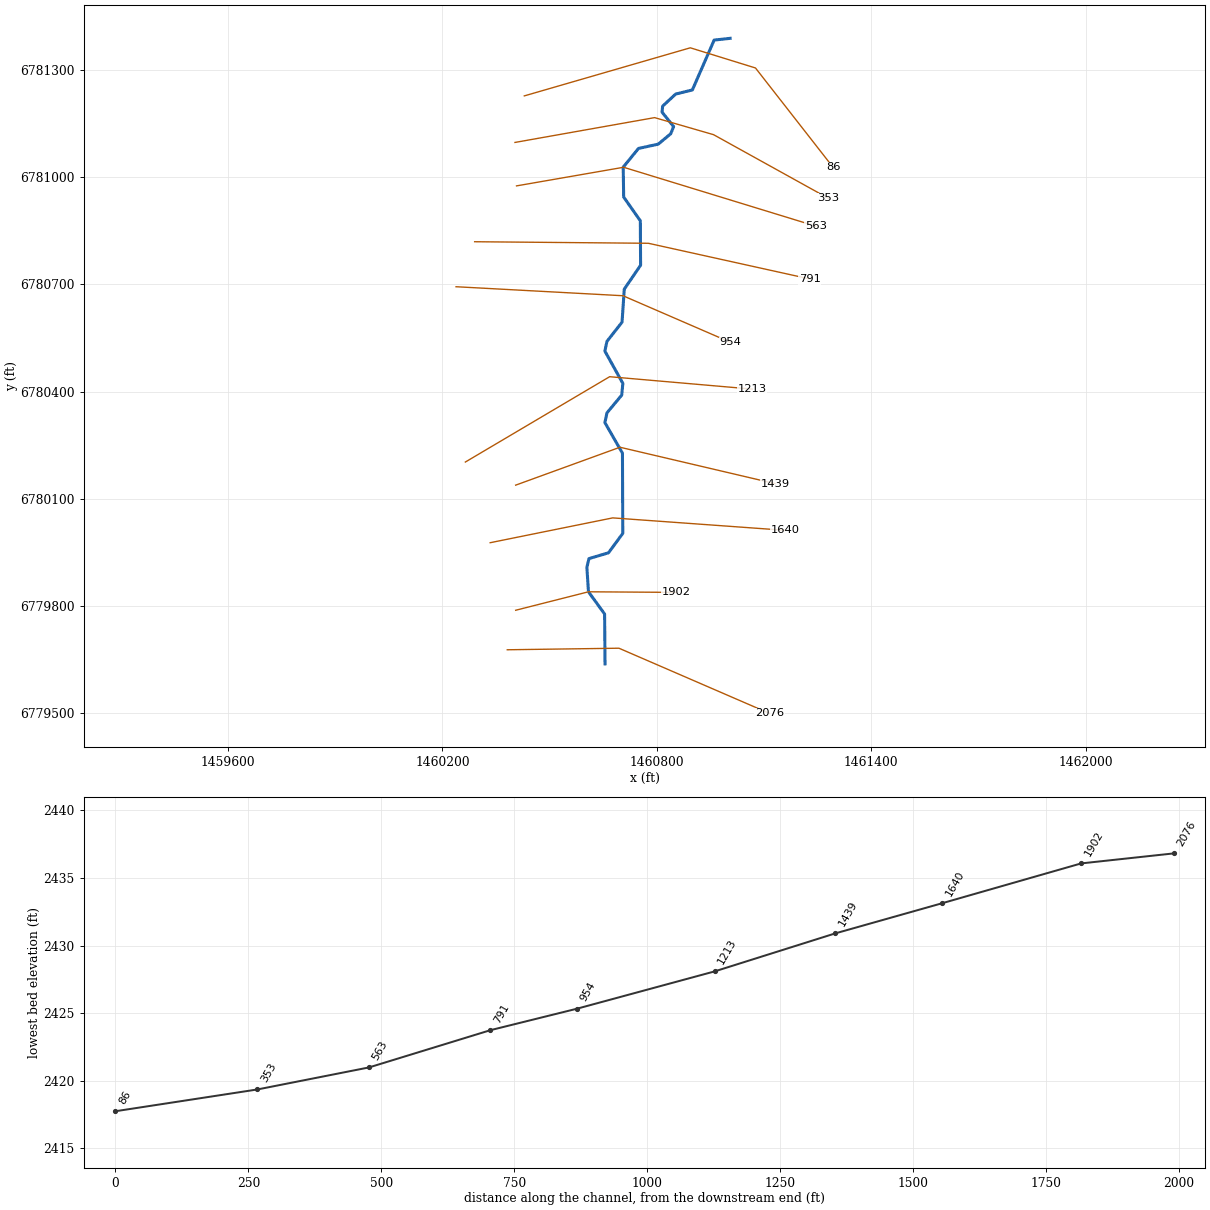
--- Elm 04.prj (project) ---

Proj Title=Elm 04 Base Level Engineering
Current Plan=p01
Default Exp/Contr=0.3,0.1
English Units
Geom File=g01
Flow File=f01
Plan File=p01
BEGIN DESCRIPTION:
Elm 04
END DESCRIPTION:

--- Elm 04.p01 (plan) ---

Plan Title=Multiple Run
Short Identifier=Multiple
Geom File=g01
Flow File=f01
Subcritical Flow
K Sum by GR= 0
Std Step Tol= 0.01
Critical Tol= 0.01
Num of Std Step Trials= 20
Max Error Tol= 0.3
Flow Tol Ratio= 0.001
Split Flow NTrial= 30
Split Flow Tol= 0.02
Split Flow Ratio= 0.02
Log Output Level= 0
Friction Slope Method= 1
Unsteady Friction Slope Method= 2
Unsteady Bridges Friction Slope Method= 1
Parabolic Critical Depth
Global Vel Dist=  1 , 1 , 1
Global Log Level= 0
CheckData=True
Encroach Param= -1, 0, 0, 0
BEGIN DESCRIPTION:
Multiple Run
END DESCRIPTION:

--- Elm 04.f01 (steady flow) ---

Flow Title=Multiple
Number of Profiles=7
Profile Names=10-year,25-year,50-year,1pct_min,100-year,1pct_plu,500-year
River Rch & RM= Elm 04,Reach-1,2076
     163     221     267     201     322     443     472
Boundary for River Rch & Prof#=Elm 04,Reach-1,1
Up Type=0
Dn Type=3
Dn Slope=0.005
Boundary for River Rch & Prof#=Elm 04,Reach-1,2
Up Type=0
Dn Type=3
Dn Slope=0.005
Boundary for River Rch & Prof#=Elm 04,Reach-1,3
Up Type=0
Dn Type=3
Dn Slope=0.005
Boundary for River Rch & Prof#=Elm 04,Reach-1,4
Up Type=0
Dn Type=3
Dn Slope=0.005
Boundary for River Rch & Prof#=Elm 04,Reach-1,5
Up Type=0
Dn Type=3
Dn Slope=0.005
Boundary for River Rch & Prof#=Elm 04,Reach-1,6
Up Type=0
Dn Type=3
Dn Slope=0.005
Boundary for River Rch & Prof#=Elm 04,Reach-1,7
Up Type=0
Dn Type=3
Dn Slope=0.005

--- Elm 04.g01 (geometry) ---

Geom Title=Existing Conditions

River Reach=Elm 04,Reach-1
Reach XY= 30
      1460655.00      6779638.00      1460653.83      6779777.52
      1460608.67      6779839.67      1460604.23      6779908.33
      1460610.14      6779932.52      1460664.75      6779948.75
      1460704.66      6780003.04      1460703.76      6780227.50
      1460654.61      6780313.00      1460660.41      6780340.20
      1460701.59      6780389.72      1460704.89      6780422.61
      1460654.61      6780513.00      1460660.37      6780540.18
      1460702.62      6780593.97      1460708.86      6780686.40
      1460754.50      6780753.22      1460753.79      6780877.49
      1460707.16      6780943.98      1460705.87      6781027.67
      1460748.66      6781079.98      1460803.79      6781091.99
      1460838.76      6781120.96      1460846.91      6781141.16
      1460814.58      6781181.46      1460816.17      6781198.29
      1460852.50      6781232.01      1460899.35      6781243.61
      1460960.28      6781383.10      1461005.00      6781388.00

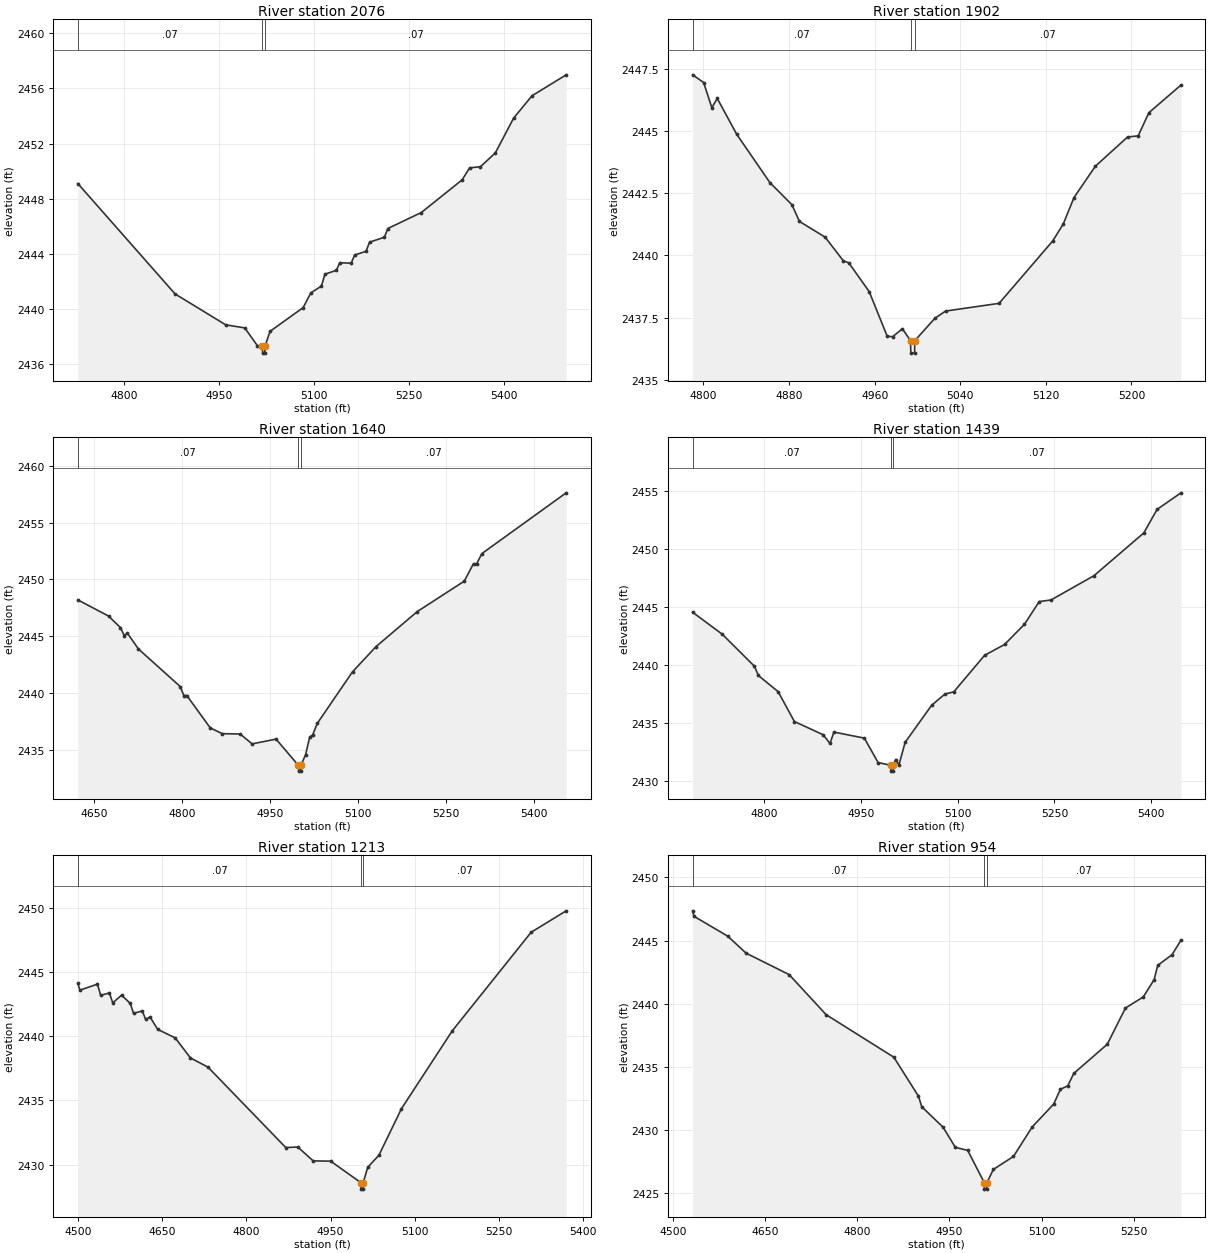
Type RM Length L Ch R = 1,2076,174,174,174
BEGIN DESCRIPTION:
elmc242
END DESCRIPTION:
XS GIS Cut Line= 3
      1460381.46      6779677.50      1460693.94      6779681.84
      1461114.96      6779499.54
#Sta/Elev= 30
  4726.8 2449.10  4880.4 2441.10  4960.4 2438.86  4990.4 2438.64  5010.4 2437.35
  5018.4 2437.31  5018.6 2436.81  5022.1 2436.81  5022.4 2437.31  5030.4 2438.39
  5082.7 2440.11  5094.9 2441.18  5111.6 2441.67  5117.0 2442.53  5135.1 2442.81
  5140.5 2443.36  5158.5 2443.33  5164.0 2443.92  5182.0 2444.19  5187.5 2444.85
  5211.0 2445.21  5216.4 2445.84  5269.3 2447.00  5333.8 2449.37  5345.6 2450.24
  5362.7 2450.32  5386.2 2451.32  5415.2 2453.85  5444.1 2455.46  5498.1 2456.98
#Mann=3,-1,0
  4726.8    0.07       0  5018.4    0.07       0  5022.4    0.07       0
Bank Sta=5018.4,5022.4
Exp/Cntr=0.3,0.1

Type RM Length L Ch R = 1,1902,262,262,262
BEGIN DESCRIPTION:
elmc198
END DESCRIPTION:
XS GIS Cut Line= 3
      1460405.02      6779788.00      1460608.67      6779839.67
      1460854.96      6779838.00
#Sta/Elev= 30
  4789.9 2447.25  4800.2 2446.94  4807.8 2445.93  4812.9 2446.30  4831.1 2444.86
  4862.1 2442.92  4882.7 2442.03  4889.7 2441.36  4913.7 2440.73  4930.7 2439.78
  4935.8 2439.70  4954.9 2438.54  4971.7 2436.75  4976.8 2436.73  4985.9 2437.05
  4993.5 2436.57  4993.8 2436.07  4997.3 2436.07  4997.5 2436.57  5016.3 2437.47
  5026.3 2437.76  5076.3 2438.07  5126.3 2440.57  5136.3 2441.26  5146.3 2442.32
  5166.3 2443.58  5196.3 2444.75  5206.3 2444.80  5216.3 2445.73  5246.3 2446.84
#Mann=3,-1,0
  4789.9    0.07       0  4993.5    0.07       0  4997.5    0.07       0
Bank Sta=4993.5,4997.5
Exp/Cntr=0.3,0.1

Type RM Length L Ch R = 1,1640,201,201,201
BEGIN DESCRIPTION:
elmc241
END DESCRIPTION:
XS GIS Cut Line= 3
      1460333.72      6779976.98      1460676.58      6780046.42
      1461158.31      6780011.70
#Sta/Elev= 30
  4622.2 2448.20  4674.5 2446.78  4694.9 2445.76  4701.5 2445.04  4706.6 2445.28
  4725.5 2443.88  4797.0 2440.56  4802.9 2439.78  4808.0 2439.78  4848.0 2436.93
  4868.4 2436.42  4899.0 2436.39  4919.4 2435.52  4960.2 2435.94  4998.5 2433.62
  4998.8 2433.12  5002.3 2433.12  5002.5 2433.62  5010.5 2434.55  5017.6 2436.12
  5022.6 2436.30  5030.6 2437.33  5090.7 2441.87  5130.8 2444.09  5201.0 2447.17
  5281.2 2449.85  5297.0 2451.40  5302.1 2451.36  5311.3 2452.28  5455.0 2457.63
#Mann=3,-1,0
  4622.2    0.07       0  4998.5    0.07       0  5002.5    0.07       0
Bank Sta=4998.5,5002.5
Exp/Cntr=0.3,0.1

Type RM Length L Ch R = 1,1439,226,226,226
BEGIN DESCRIPTION:
elmc197
END DESCRIPTION:
XS GIS Cut Line= 3
      1460404.99      6780138.00      1460696.81      6780244.08
      1461131.12      6780142.18
#Sta/Elev= 30
  4689.5 2444.56  4735.4 2442.67  4785.3 2439.91  4791.3 2439.12  4821.9 2437.73
  4847.1 2435.16  4891.7 2434.02  4902.3 2433.27  4908.3 2434.25  4955.5 2433.73
  4976.8 2431.63  4996.4 2431.39  4996.7 2430.89  5000.2 2430.89  5000.4 2431.39
  5004.0 2431.89  5009.1 2431.43  5018.7 2433.37  5059.8 2436.56  5080.3 2437.52
  5094.0 2437.71  5141.9 2440.86  5172.8 2441.79  5203.6 2443.53  5226.4 2445.48
  5244.7 2445.62  5311.3 2447.71  5388.5 2451.39  5409.0 2453.41  5446.1 2454.84
#Mann=3,-1,0
  4689.5    0.07       0  4996.4    0.07       0  5000.4    0.07       0
Bank Sta=4996.4,5000.4
Exp/Cntr=0.3,0.1

Type RM Length L Ch R = 1,1213,259,259,259
BEGIN DESCRIPTION:
elmc240
END DESCRIPTION:
XS GIS Cut Line= 3
      1460264.27      6780202.68      1460667.90      6780441.39
      1461067.16      6780406.67
#Sta/Elev= 30
  4499.8 2444.13  4503.4 2443.59  4534.7 2444.06  4540.5 2443.19  4556.1 2443.37
  4562.0 2442.60  4577.6 2443.20  4593.2 2442.56  4599.0 2441.79  4614.7 2441.97
  4620.5 2441.31  4628.4 2441.50  4641.9 2440.54  4673.2 2439.87  4700.4 2438.31
  4731.7 2437.59  4870.1 2431.33  4891.6 2431.37  4918.9 2430.29  4950.1 2430.27
  5004.0 2428.59  5004.2 2428.09  5007.7 2428.09  5008.0 2428.59  5016.0 2429.78
  5036.1 2430.74  5076.2 2434.36  5166.6 2440.42  5307.1 2448.10  5369.5 2449.77
#Mann=3,-1,0
  4499.8    0.07       0  5004.0    0.07       0  5008.0    0.07       0
Bank Sta=5004,5008
Exp/Cntr=0.3,0.1

Type RM Length L Ch R = 1,954,163,163,163
BEGIN DESCRIPTION:
elmc196
END DESCRIPTION:
XS GIS Cut Line= 3
      1460238.22      6780693.12      1460705.24      6780667.90
      1461005.00      6780538.00
#Sta/Elev= 30
  4532.3 2447.36  4534.3 2446.93  4589.2 2445.36  4619.2 2444.01  4689.3 2442.31
  4749.4 2439.14  4859.6 2435.77  4899.6 2432.69  4905.0 2431.85  4939.7 2430.23
  4959.7 2428.63  4979.7 2428.40  5006.8 2425.83  5007.0 2425.33  5010.5 2425.33
  5010.8 2425.83  5021.5 2426.89  5054.2 2427.92  5084.6 2430.25  5119.6 2432.06
  5130.5 2433.23  5142.5 2433.51  5152.3 2434.49  5206.8 2436.80  5236.4 2439.67
  5265.3 2440.54  5283.1 2441.92  5288.8 2443.04  5312.2 2443.89  5326.7 2445.04
#Mann=3,-1,0
  4532.3    0.07       0  5006.8    0.07       0  5010.8    0.07       0
Bank Sta=5006.8,5010.8
Exp/Cntr=0.3,0.1

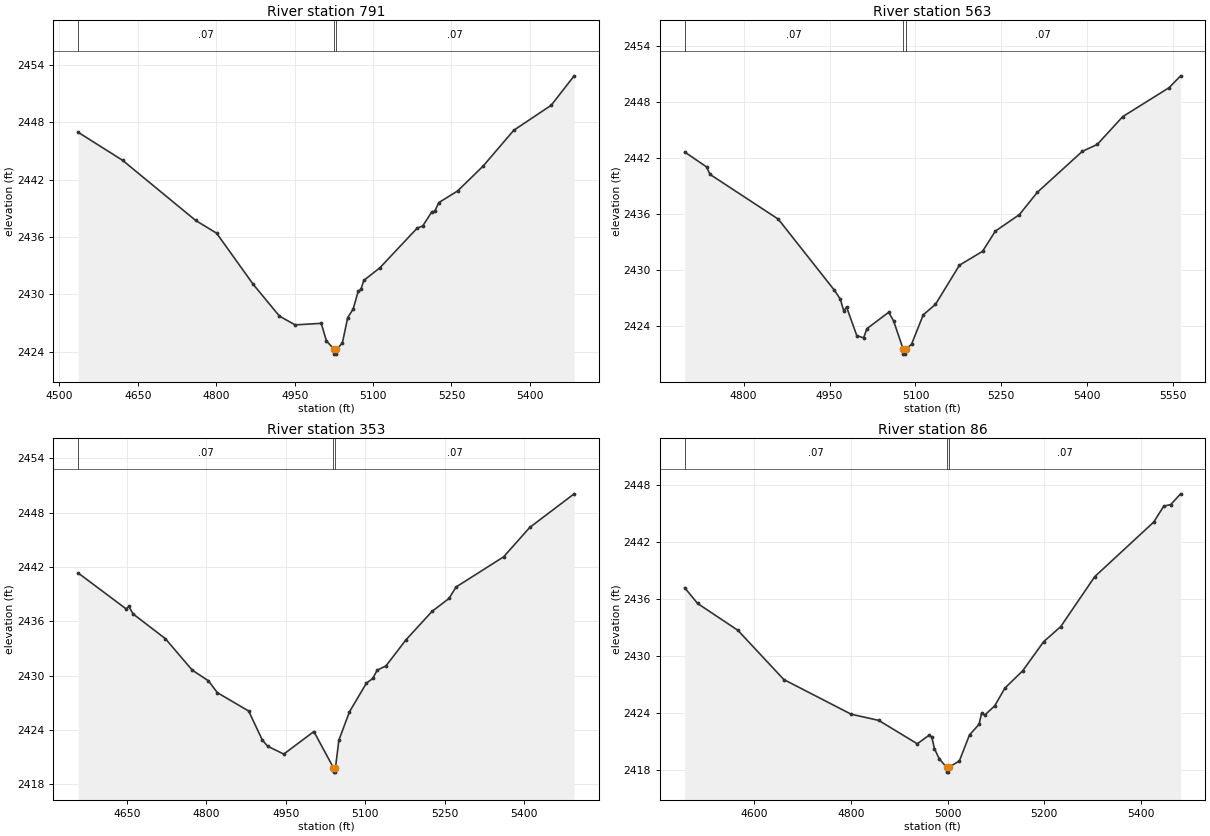
Type RM Length L Ch R = 1,791,228,228,228
BEGIN DESCRIPTION:
elmc239
END DESCRIPTION:
XS GIS Cut Line= 3
      1460290.26      6780818.99      1460776.40      6780814.65
      1461227.84      6780714.81
#Sta/Elev= 30
  4536.1 2446.94  4620.8 2444.02  4760.8 2437.72  4800.8 2436.39  4870.8 2431.04
  4920.9 2427.72  4950.9 2426.80  5000.9 2426.96  5010.9 2425.11  5025.9 2424.24
  5026.2 2423.74  5029.7 2423.74  5029.9 2424.24  5041.3 2424.90  5051.5 2427.56
  5061.8 2428.44  5071.6 2430.31  5076.7 2430.51  5082.3 2431.45  5113.0 2432.77
  5184.7 2436.94  5194.9 2437.14  5212.7 2438.65  5217.8 2438.66  5225.7 2439.59
  5261.5 2440.80  5310.2 2443.39  5369.0 2447.15  5440.7 2449.77  5484.6 2452.85
#Mann=3,-1,0
  4536.1    0.07       0  5025.9    0.07       0  5029.9    0.07       0
Bank Sta=5025.9,5029.9
Exp/Cntr=0.3,0.1

Type RM Length L Ch R = 1,563,210,210,210
BEGIN DESCRIPTION:
elmc195
END DESCRIPTION:
XS GIS Cut Line= 3
      1460407.44      6780975.23      1460706.96      6781027.32
      1461244.18      6780862.69
#Sta/Elev= 30
  4697.1 2442.66  4735.2 2441.07  4741.4 2440.26  4860.6 2435.46  4958.5 2427.84
  4968.7 2426.90  4974.8 2425.64  4979.9 2426.02  4997.6 2422.97  5009.5 2422.74
  5015.3 2423.72  5053.3 2425.48  5061.8 2424.56  5078.8 2421.49  5079.1 2420.99
  5082.6 2420.99  5082.8 2421.49  5093.2 2422.05  5113.6 2425.20  5135.0 2426.33
  5176.9 2430.53  5217.1 2432.01  5239.6 2434.18  5281.5 2435.95  5312.8 2438.34
  5391.3 2442.73  5417.4 2443.47  5462.0 2446.46  5542.9 2449.56  5563.0 2450.83
#Mann=3,-1,0
  4697.1    0.07       0  5078.8    0.07       0  5082.8    0.07       0
Bank Sta=5078.8,5082.8
Exp/Cntr=0.3,0.1

Type RM Length L Ch R = 1,353,267,267,267
BEGIN DESCRIPTION:
elmc238
END DESCRIPTION:
XS GIS Cut Line= 4
      1460403.11      6781096.76      1460793.76      6781166.21
      1460958.69      6781118.47      1461279.90      6780940.50
#Sta/Elev= 30
  4558.4 2441.33  4648.9 2437.37  4654.0 2437.64  4661.9 2436.82  4722.8 2434.09
  4773.6 2430.61  4804.1 2429.44  4820.9 2428.13  4880.0 2426.10  4905.7 2422.91
  4915.8 2422.22  4946.3 2421.35  5003.0 2423.84  5039.8 2419.86  5040.1 2419.36
  5043.6 2419.36  5043.8 2419.86  5050.2 2422.89  5070.2 2426.02  5102.2 2429.18
  5114.2 2429.70  5122.4 2430.61  5139.0 2431.08  5176.8 2433.96  5226.0 2437.10
  5258.1 2438.53  5271.3 2439.79  5361.1 2443.12  5410.3 2446.36  5494.1 2450.07
#Mann=3,-1,0
  4558.4    0.07       0  5039.8    0.07       0  5043.8    0.07       0
Bank Sta=5039.8,5043.8
Exp/Cntr=0.3,0.1

Type RM Length L Ch R = 1,86,0,0,0
BEGIN DESCRIPTION:
elmc237
END DESCRIPTION:
XS GIS Cut Line= 4
      1460429.18      6781226.98      1460893.59      6781361.52
      1461075.88      6781305.10      1461292.88      6781027.35
#Sta/Elev= 30
  4455.6 2437.20  4482.5 2435.54  4565.8 2432.71  4660.8 2427.52  4800.3 2423.86
  4857.3 2423.21  4937.2 2420.74  4961.5 2421.64  4967.3 2421.45  4972.6 2420.24
  4982.5 2419.17  4998.0 2418.25  4998.2 2417.75  5001.7 2417.75  5002.0 2418.25
  5024.3 2418.93  5045.3 2421.68  5065.2 2422.80  5070.4 2423.99  5076.7 2423.76
  5097.6 2424.75  5118.5 2426.61  5155.4 2428.44  5198.8 2431.51  5234.1 2433.10
  5304.7 2438.38  5426.7 2444.13  5447.5 2445.81  5462.0 2445.98  5482.4 2447.11
#Mann=3,-1,0
  4455.6    0.07       0  4998.0    0.07       0  5002.0    0.07       0
Bank Sta=4998,5002
Exp/Cntr=0.3,0.1

Chan Stop Cuts=-1