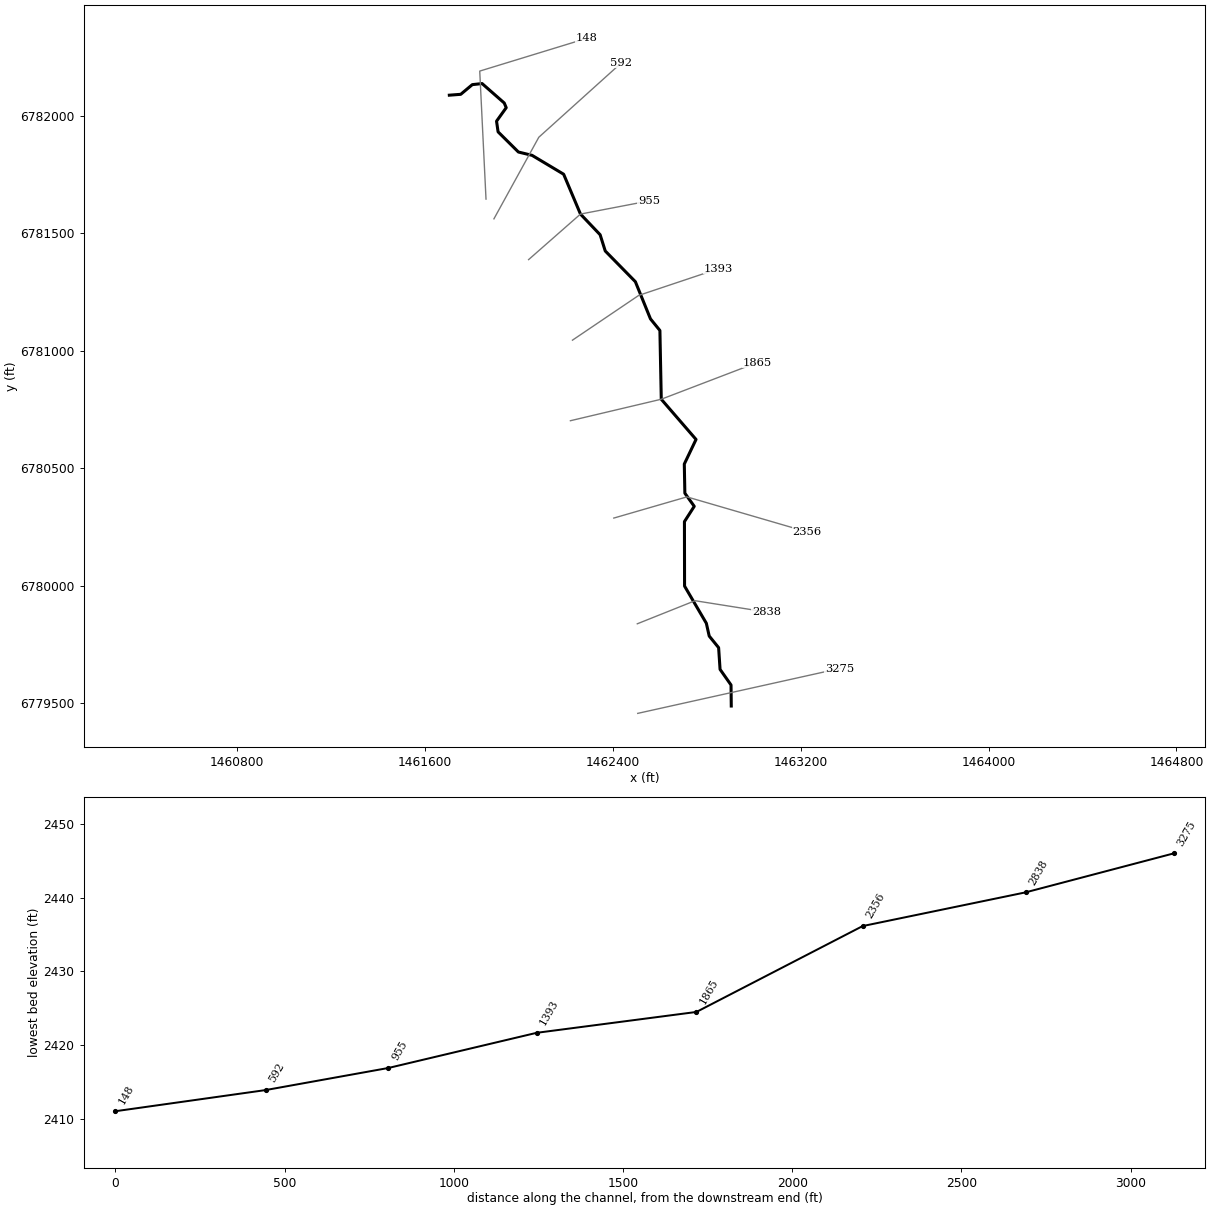
--- Elm 05.prj (project) ---

Proj Title=Elm 05 Base Level Engineering
Current Plan=p01
Default Exp/Contr=0.3,0.1
English Units
Geom File=g01
Flow File=f01
Plan File=p01
BEGIN DESCRIPTION:
Elm 05
END DESCRIPTION:

--- Elm 05.p01 (plan) ---

Plan Title=Multiple Run
Short Identifier=Multiple
Geom File=g01
Flow File=f01
Subcritical Flow
K Sum by GR= 0
Std Step Tol= 0.01
Critical Tol= 0.01
Num of Std Step Trials= 20
Max Error Tol= 0.3
Flow Tol Ratio= 0.001
Split Flow NTrial= 30
Split Flow Tol= 0.02
Split Flow Ratio= 0.02
Log Output Level= 0
Friction Slope Method= 1
Unsteady Friction Slope Method= 2
Unsteady Bridges Friction Slope Method= 1
Parabolic Critical Depth
Global Vel Dist=  1 , 1 , 1
Global Log Level= 0
CheckData=True
Encroach Param= -1, 0, 0, 0
BEGIN DESCRIPTION:
Multiple Run
END DESCRIPTION:

--- Elm 05.f01 (steady flow) ---

Flow Title=Multiple
Number of Profiles=7
Profile Names=10-year,25-year,50-year,1pct_min,100-year,1pct_plu,500-year
River Rch & RM= Elm 05,Reach-1,3275
     162     220     267     201     322     444     475
Boundary for River Rch & Prof#=Elm 05,Reach-1,1
Up Type=0
Dn Type=3
Dn Slope=0.005
Boundary for River Rch & Prof#=Elm 05,Reach-1,2
Up Type=0
Dn Type=3
Dn Slope=0.005
Boundary for River Rch & Prof#=Elm 05,Reach-1,3
Up Type=0
Dn Type=3
Dn Slope=0.005
Boundary for River Rch & Prof#=Elm 05,Reach-1,4
Up Type=0
Dn Type=3
Dn Slope=0.005
Boundary for River Rch & Prof#=Elm 05,Reach-1,5
Up Type=0
Dn Type=3
Dn Slope=0.005
Boundary for River Rch & Prof#=Elm 05,Reach-1,6
Up Type=0
Dn Type=3
Dn Slope=0.005
Boundary for River Rch & Prof#=Elm 05,Reach-1,7
Up Type=0
Dn Type=3
Dn Slope=0.005

--- Elm 05.g01 (geometry) ---

Geom Title=Existing Conditions

River Reach=Elm 05,Reach-1
Reach XY= 30
      1462905.00      6779488.00      1462903.98      6779577.58
      1462857.33      6779643.97      1462851.17      6779736.42
      1462811.12      6779785.82      1462798.92      6779840.20
      1462706.20      6779998.50      1462705.66      6780272.84
      1462747.44      6780338.00      1462707.45      6780393.86
      1462705.07      6780517.97      1462755.05      6780622.66
      1462607.06      6780793.85      1462601.25      6781086.45
      1462561.12      6781135.82      1462496.86      6781294.06
      1462368.63      6781424.79      1462346.82      6781494.04
      1462263.16      6781581.95      1462191.53      6781751.57
      1462057.19      6781831.90      1461998.92      6781846.13
      1461912.49      6781931.93      1461905.89      6781977.36
      1461947.09      6782034.78      1461938.71      6782054.74
      1461844.40      6782137.44      1461802.76      6782132.91
      1461753.51      6782091.69      1461705.00      6782088.00

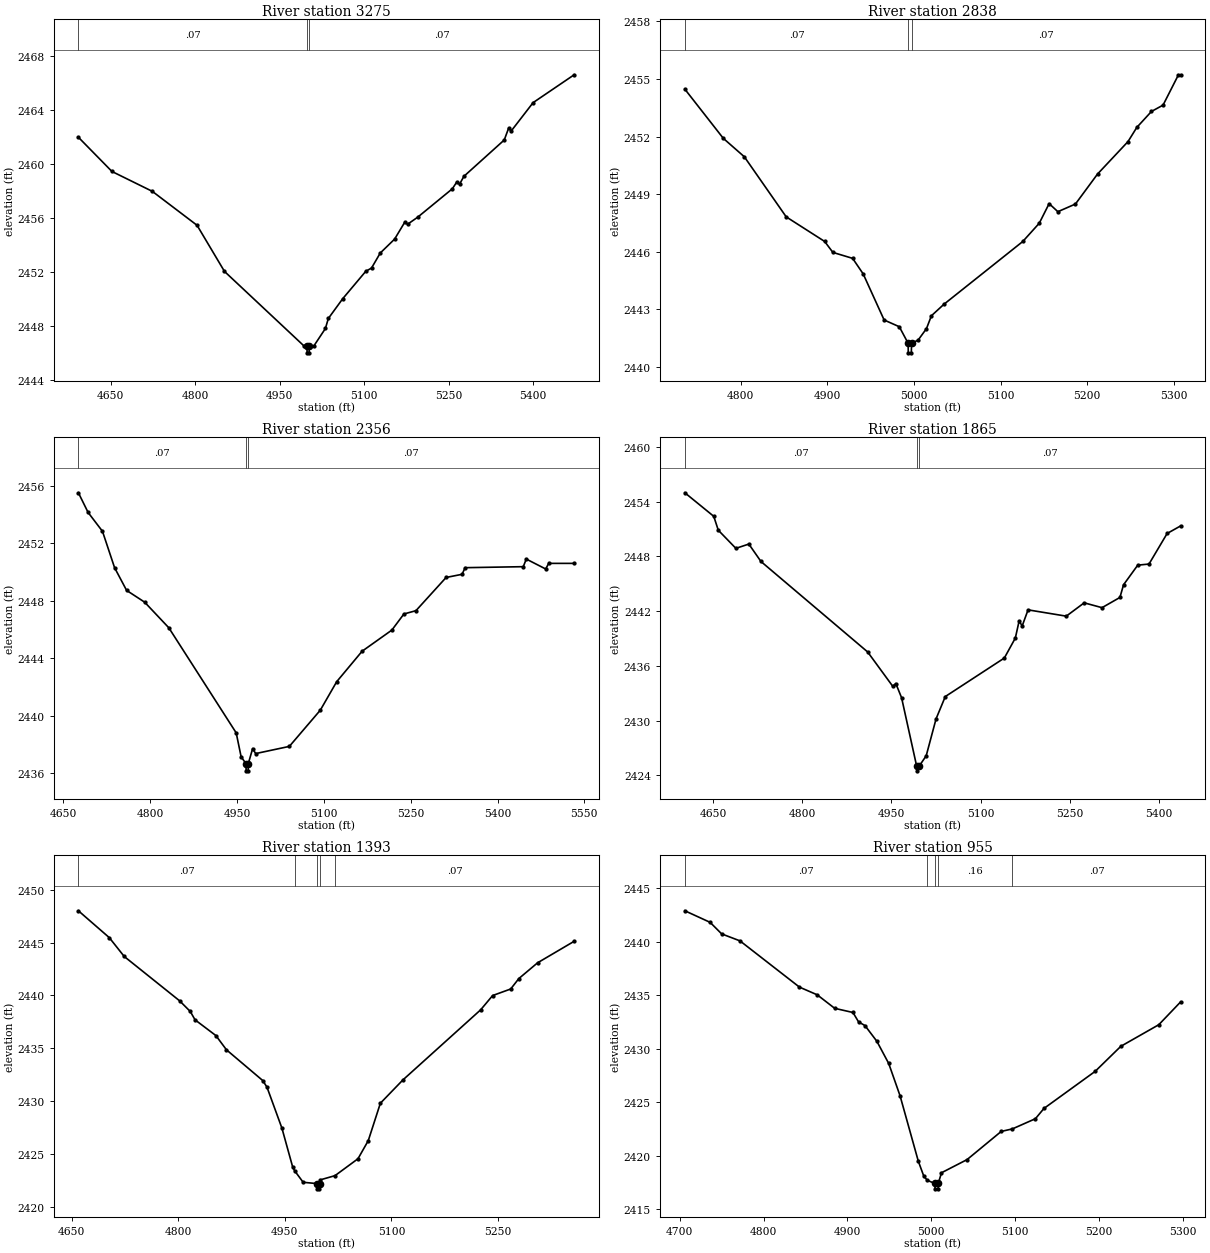
Type RM Length L Ch R = 1,3275,437,437,437
BEGIN DESCRIPTION:
elmc244
END DESCRIPTION:
XS GIS Cut Line= 2
      1462506.85      6779456.71      1463366.18      6779647.68
#Sta/Elev= 30
  4592.8 2461.96  4652.4 2459.43  4724.1 2457.96  4803.5 2455.45  4852.2 2452.04
  4993.1 2446.54  4998.7 2446.52  4998.9 2446.02  5002.4 2446.02  5002.7 2446.52
  5010.9 2446.53  5031.4 2447.82  5036.6 2448.56  5062.1 2450.02  5103.1 2452.05
  5113.3 2452.29  5128.8 2453.40  5154.3 2454.43  5172.3 2455.68  5177.4 2455.53
  5195.3 2456.05  5256.8 2458.15  5264.5 2458.64  5269.6 2458.49  5277.3 2459.07
  5349.0 2461.76  5356.7 2462.63  5361.8 2462.45  5400.2 2464.52  5473.1 2466.58
#Mann=3,-1,0
  4592.8    0.07       0  4998.7    0.07       0  5002.7    0.07       0
Bank Sta=4998.7,5002.7
Exp/Cntr=0.3,0.1

Type RM Length L Ch R = 1,2838,482,482,482
BEGIN DESCRIPTION:
elmc204
END DESCRIPTION:
XS GIS Cut Line= 3
      1462505.02      6779838.01      1462750.81      6779936.26
      1463055.00      6779888.00
#Sta/Elev= 30
  4735.3 2454.47  4779.7 2451.91  4804.0 2450.95  4852.4 2447.82  4896.8 2446.54
  4906.3 2445.97  4929.1 2445.66  4941.3 2444.85  4965.5 2442.45  4983.0 2442.10
  4993.2 2441.24  4993.4 2440.74  4996.9 2440.74  4997.2 2441.24  5004.7 2441.40
  5014.4 2442.00  5020.1 2442.67  5034.6 2443.27  5125.7 2446.54  5144.7 2447.49
  5156.1 2448.51  5166.2 2448.09  5186.5 2448.49  5212.0 2450.05  5247.2 2451.74
  5257.4 2452.48  5274.3 2453.31  5287.7 2453.64  5305.5 2455.22  5308.0 2455.22
#Mann=3,-1,0
  4735.3    0.07       0  4993.2    0.07       0  4997.2    0.07       0
Bank Sta=4993.2,4997.2
Exp/Cntr=0.3,0.1

Type RM Length L Ch R = 1,2356,491,491,491
BEGIN DESCRIPTION:
elmc203
END DESCRIPTION:
XS GIS Cut Line= 3
      1462405.01      6780288.00      1462716.20      6780378.21
      1463227.35      6780229.27
#Sta/Elev= 30
  4676.0 2455.50  4692.8 2454.13  4717.6 2452.82  4738.5 2450.29  4759.3 2448.71
  4790.5 2447.89  4832.2 2446.11  4948.6 2438.80  4957.1 2437.14  4965.5 2436.66
  4965.8 2436.16  4969.3 2436.16  4969.5 2436.66  4977.0 2437.71  4982.2 2437.36
  5040.4 2437.86  5093.9 2440.38  5122.2 2442.36  5166.1 2444.48  5217.5 2445.95
  5238.3 2447.07  5259.1 2447.30  5311.2 2449.61  5338.8 2449.83  5344.0 2450.29
  5444.5 2450.36  5449.7 2450.89  5483.2 2450.20  5488.4 2450.59  5532.4 2450.59
#Mann=3,-1,0
  4676.0    0.07       0  4965.5    0.07       0  4969.5    0.07       0
Bank Sta=4965.5,4969.5
Exp/Cntr=0.3,0.1

Type RM Length L Ch R = 1,1865,472,472,472
BEGIN DESCRIPTION:
elmc202
END DESCRIPTION:
XS GIS Cut Line= 3
      1462220.33      6780702.36      1462607.06      6780793.85
      1463014.65      6780949.77
#Sta/Elev= 30
  4602.6 2454.98  4651.2 2452.40  4658.8 2450.88  4688.4 2448.89  4710.2 2449.36
  4730.6 2447.45  4910.0 2437.54  4952.3 2433.77  4957.4 2434.08  4967.1 2432.52
  4992.5 2425.01  4992.8 2424.51  4996.5 2425.01  5008.5 2426.16  5025.1 2430.21
  5040.6 2432.65  5139.9 2436.87  5158.4 2439.06  5164.7 2440.91  5170.0 2440.40
  5179.8 2442.15  5244.1 2441.46  5274.2 2442.92  5304.2 2442.39  5334.3 2443.51
  5340.4 2444.90  5364.3 2447.05  5383.2 2447.17  5413.7 2450.52  5436.4 2451.35
#Mann=3,-1,0
  4602.6    0.07       0  4992.5    0.07       0  4996.5    0.07       0
Bank Sta=4992.5,4996.5
Exp/Cntr=0.3,0.1

Type RM Length L Ch R = 1,1393,438,438,438
BEGIN DESCRIPTION:
elmc201
END DESCRIPTION:
XS GIS Cut Line= 3
      1462229.05      6781045.25      1462511.10      6781235.81
      1462849.67      6781349.06
#Sta/Elev= 30
  4659.6 2448.02  4703.0 2445.48  4724.1 2443.69  4802.0 2439.49  4817.0 2438.48
  4823.7 2437.69  4853.0 2436.20  4867.9 2434.85  4918.9 2431.94  4924.9 2431.31
  4945.9 2427.43  4960.9 2423.78  4963.7 2423.40  4975.8 2422.30  4994.8 2422.18
  4995.1 2421.68  4998.6 2421.68  4998.8 2422.18  4999.3 2422.52  5020.6 2422.93
  5052.9 2424.53  5067.4 2426.25  5084.4 2429.79  5116.0 2431.99  5225.5 2438.64
  5242.3 2439.99  5267.7 2440.61  5279.2 2441.60  5305.5 2443.09  5357.0 2445.13
#Mann=5,-1,0
  4659.6    0.07       0  4963.7    0.16       0  4994.8    0.07       0
  4998.8    0.16       0  5020.6    0.07       0
Bank Sta=4994.8,4998.8
Exp/Cntr=0.3,0.1

Type RM Length L Ch R = 1,955,363,363,363
BEGIN DESCRIPTION:
elmc200
END DESCRIPTION:
XS GIS Cut Line= 3
      1462042.38      6781388.10      1462263.16      6781581.95
      1462555.02      6781638.00
#Sta/Elev= 30
  4706.2 2442.88  4736.3 2441.80  4750.1 2440.72  4771.9 2440.07  4842.8 2435.75
  4864.0 2435.03  4884.8 2433.77  4906.6 2433.38  4913.3 2432.50  4920.9 2432.16
  4935.1 2430.69  4949.2 2428.62  4962.7 2425.61  4984.5 2419.49  4991.1 2418.08
  4995.4 2417.70  5004.3 2417.41  5004.5 2416.91  5008.0 2416.91  5008.3 2417.41
  5012.1 2418.41  5042.6 2419.64  5083.3 2422.27  5096.7 2422.51  5124.1 2423.46
  5134.3 2424.42  5195.3 2427.88  5225.9 2430.22  5271.2 2432.24  5297.2 2434.37
#Mann=5,-1,0
  4706.2    0.07       0  4995.4    0.16       0  5004.3    0.07       0
  5008.3    0.16       0  5096.7    0.07       0
Bank Sta=5004.3,5008.3
Exp/Cntr=0.3,0.1

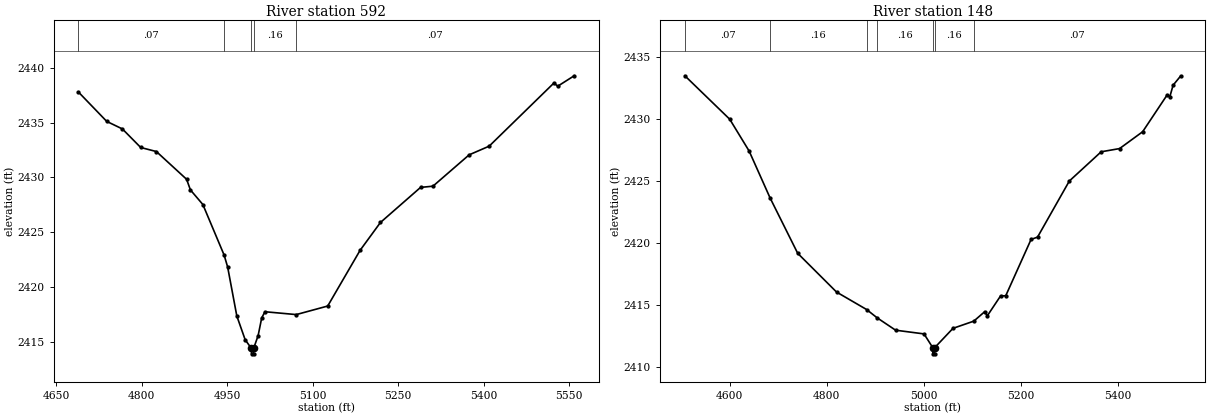
Type RM Length L Ch R = 1,592,444,444,444
BEGIN DESCRIPTION:
elmc243
END DESCRIPTION:
XS GIS Cut Line= 3
      1461894.83      6781561.72      1462085.82      6781908.96
      1462437.40      6782225.82
#Sta/Elev= 30
  4689.0 2437.79  4738.7 2435.11  4766.2 2434.42  4798.3 2432.73  4825.8 2432.36
  4878.8 2429.83  4885.5 2428.86  4907.3 2427.53  4944.6 2422.92  4950.8 2421.83
  4966.9 2417.36  4981.5 2415.20  4992.4 2414.41  4992.7 2413.91  4996.2 2413.91
  4996.4 2414.41  5004.3 2415.58  5010.5 2417.18  5016.2 2417.75  5071.1 2417.49
  5126.3 2418.27  5183.1 2423.35  5218.8 2425.89  5289.2 2429.09  5310.9 2429.20
  5374.4 2432.06  5409.5 2432.85  5523.1 2438.61  5529.8 2438.32  5558.6 2439.27
#Mann=5,-1,0
  4689.0    0.07       0  4944.6    0.16       0  4992.4    0.07       0
  4996.4    0.16       0  5071.1    0.07       0
Bank Sta=4992.4,4996.4
Exp/Cntr=0.3,0.1

Type RM Length L Ch R = 1,148,0,0,0
BEGIN DESCRIPTION:
elmc199
END DESCRIPTION:
XS GIS Cut Line= 3
      1461861.07      6781645.63      1461834.39      6782190.57
      1462289.84      6782329.98
#Sta/Elev= 30
  4507.4 2433.50  4599.9 2429.99  4639.9 2427.42  4683.1 2423.63  4740.0 2419.16
  4820.1 2416.03  4882.0 2414.62  4903.7 2413.95  4941.8 2412.95  5000.4 2412.65
  5018.4 2411.54  5018.6 2411.04  5022.1 2411.04  5022.4 2411.54  5060.1 2413.10
  5102.9 2413.68  5125.6 2414.45  5130.8 2414.11  5158.2 2415.72  5168.8 2415.73
  5221.0 2420.28  5234.4 2420.47  5299.9 2425.00  5365.5 2427.36  5403.5 2427.62
  5451.0 2428.98  5501.8 2431.97  5507.0 2431.80  5513.8 2432.74  5529.3 2433.48
#Mann=7,-1,0
  4507.4    0.07       0  4683.1    0.16       0  4882.0    0.07       0
  4903.7    0.16       0  5018.4    0.07       0  5022.4    0.16       0
  5102.9    0.07       0
Bank Sta=5018.4,5022.4
Exp/Cntr=0.3,0.1

Chan Stop Cuts=-1