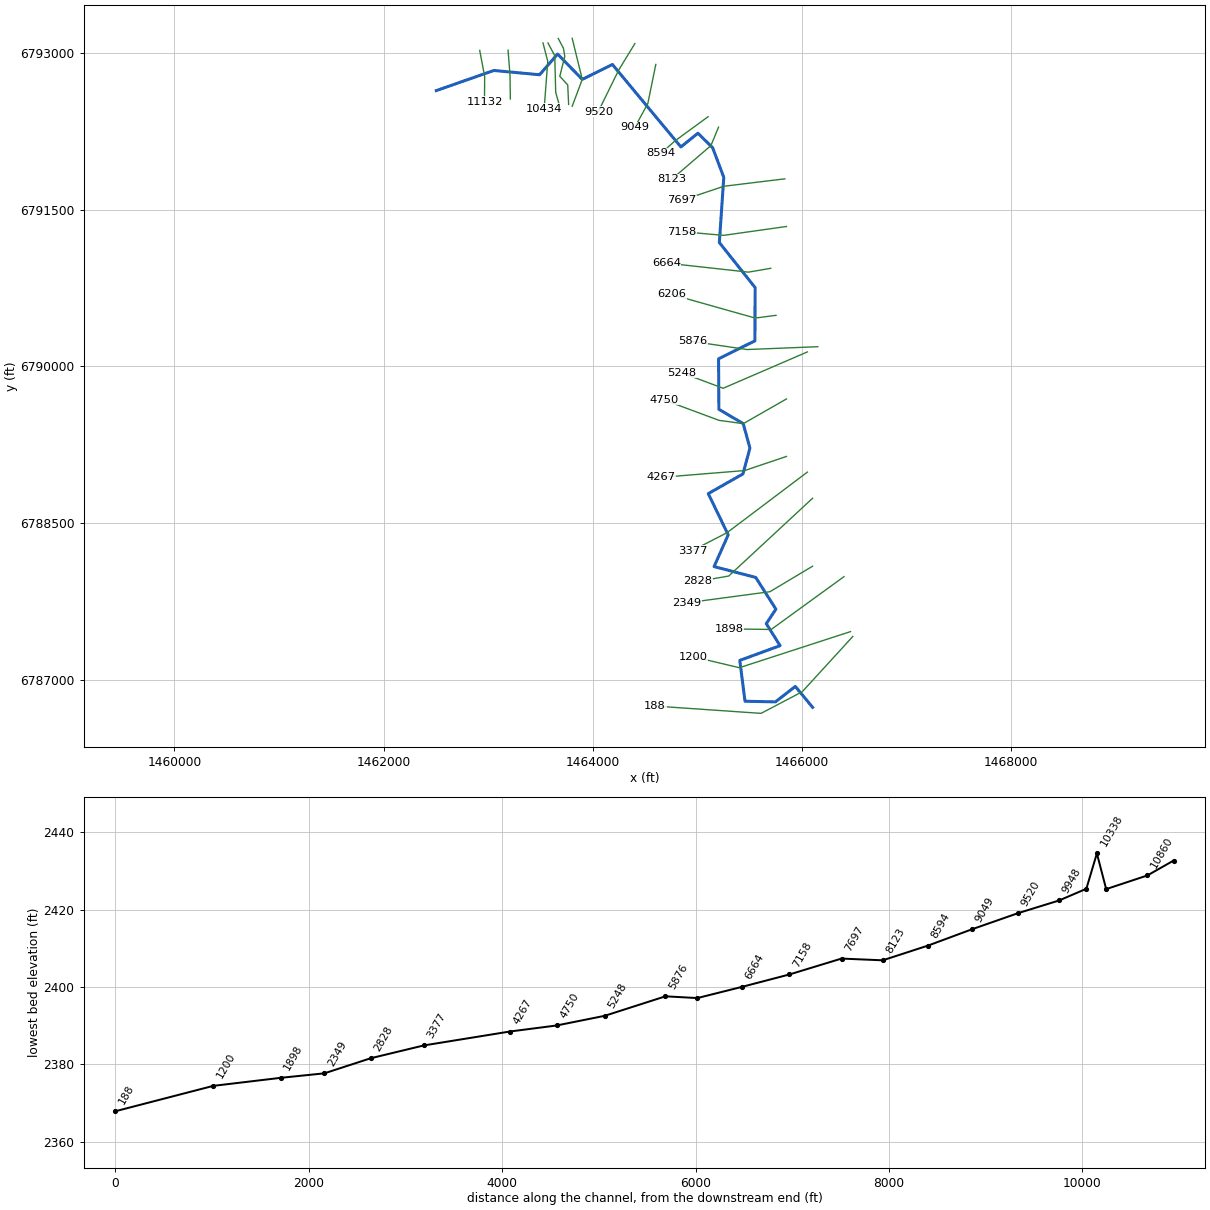
--- Elm 06.prj (project) ---

Proj Title=Elm 06 Base Level Engineering
Current Plan=p01
Default Exp/Contr=0.3,0.1
English Units
Geom File=g01
Flow File=f01
Plan File=p01
BEGIN DESCRIPTION:
Elm 06
END DESCRIPTION:

--- Elm 06.p01 (plan) ---

Plan Title=Multiple Run
Short Identifier=Multiple
Geom File=g01
Flow File=f01
Subcritical Flow
K Sum by GR= 0
Std Step Tol= 0.01
Critical Tol= 0.01
Num of Std Step Trials= 20
Max Error Tol= 0.3
Flow Tol Ratio= 0.001
Split Flow NTrial= 30
Split Flow Tol= 0.02
Split Flow Ratio= 0.02
Log Output Level= 0
Friction Slope Method= 1
Unsteady Friction Slope Method= 2
Unsteady Bridges Friction Slope Method= 1
Parabolic Critical Depth
Global Vel Dist=  1 , 1 , 1
Global Log Level= 0
CheckData=True
Encroach Param= -1, 0, 0, 0
BEGIN DESCRIPTION:
Multiple Run
END DESCRIPTION:

--- Elm 06.f01 (steady flow) ---

Flow Title=Multiple
Number of Profiles=7
Profile Names=10-year,25-year,50-year,1pct_min,100-year,1pct_plu,500-year
River Rch & RM= Elm 06,Reach-1,11132
     165     222     267     199     320     440     462
River Rch & RM= Elm 06,Reach-1,9520
     407     579     724     560     897    1230    1390
River Rch & RM= Elm 06,Reach-1,3377
     480     689     867     674    1080    1490    1700
Boundary for River Rch & Prof#=Elm 06,Reach-1,1
Up Type=0
Dn Type=3
Dn Slope=0.005
Boundary for River Rch & Prof#=Elm 06,Reach-1,2
Up Type=0
Dn Type=3
Dn Slope=0.005
Boundary for River Rch & Prof#=Elm 06,Reach-1,3
Up Type=0
Dn Type=3
Dn Slope=0.005
Boundary for River Rch & Prof#=Elm 06,Reach-1,4
Up Type=0
Dn Type=3
Dn Slope=0.005
Boundary for River Rch & Prof#=Elm 06,Reach-1,5
Up Type=0
Dn Type=3
Dn Slope=0.005
Boundary for River Rch & Prof#=Elm 06,Reach-1,6
Up Type=0
Dn Type=3
Dn Slope=0.005
Boundary for River Rch & Prof#=Elm 06,Reach-1,7
Up Type=0
Dn Type=3
Dn Slope=0.005

--- Elm 06.g01 (geometry) ---

Geom Title=Existing Conditions

River Reach=Elm 06,Reach-1
Reach XY= 30
      1462505.00      6792638.00      1463055.00      6792830.44
      1463493.17      6792789.62      1463665.64      6792987.45
      1463901.42      6792745.48      1464190.00      6792887.74
      1464845.00      6792098.95      1465008.33      6792230.41
      1465149.17      6792090.30      1465255.39      6791808.13
      1465212.81      6791184.59      1465555.44      6790753.18
      1465552.95      6790243.84      1465205.42      6790072.36
      1465208.37      6789589.28      1465441.53      6789451.57
      1465505.39      6789217.87      1465438.72      6788970.86
      1465106.88      6788782.31      1465297.68      6788388.10
      1465162.49      6788084.41      1465561.17      6787980.24
      1465753.95      6787677.34      1465662.03      6787538.21
      1465793.93      6787327.92      1465408.43      6787186.78
      1465458.35      6786796.09      1465749.35      6786789.97
      1465939.82      6786937.64      1466105.00      6786738.00

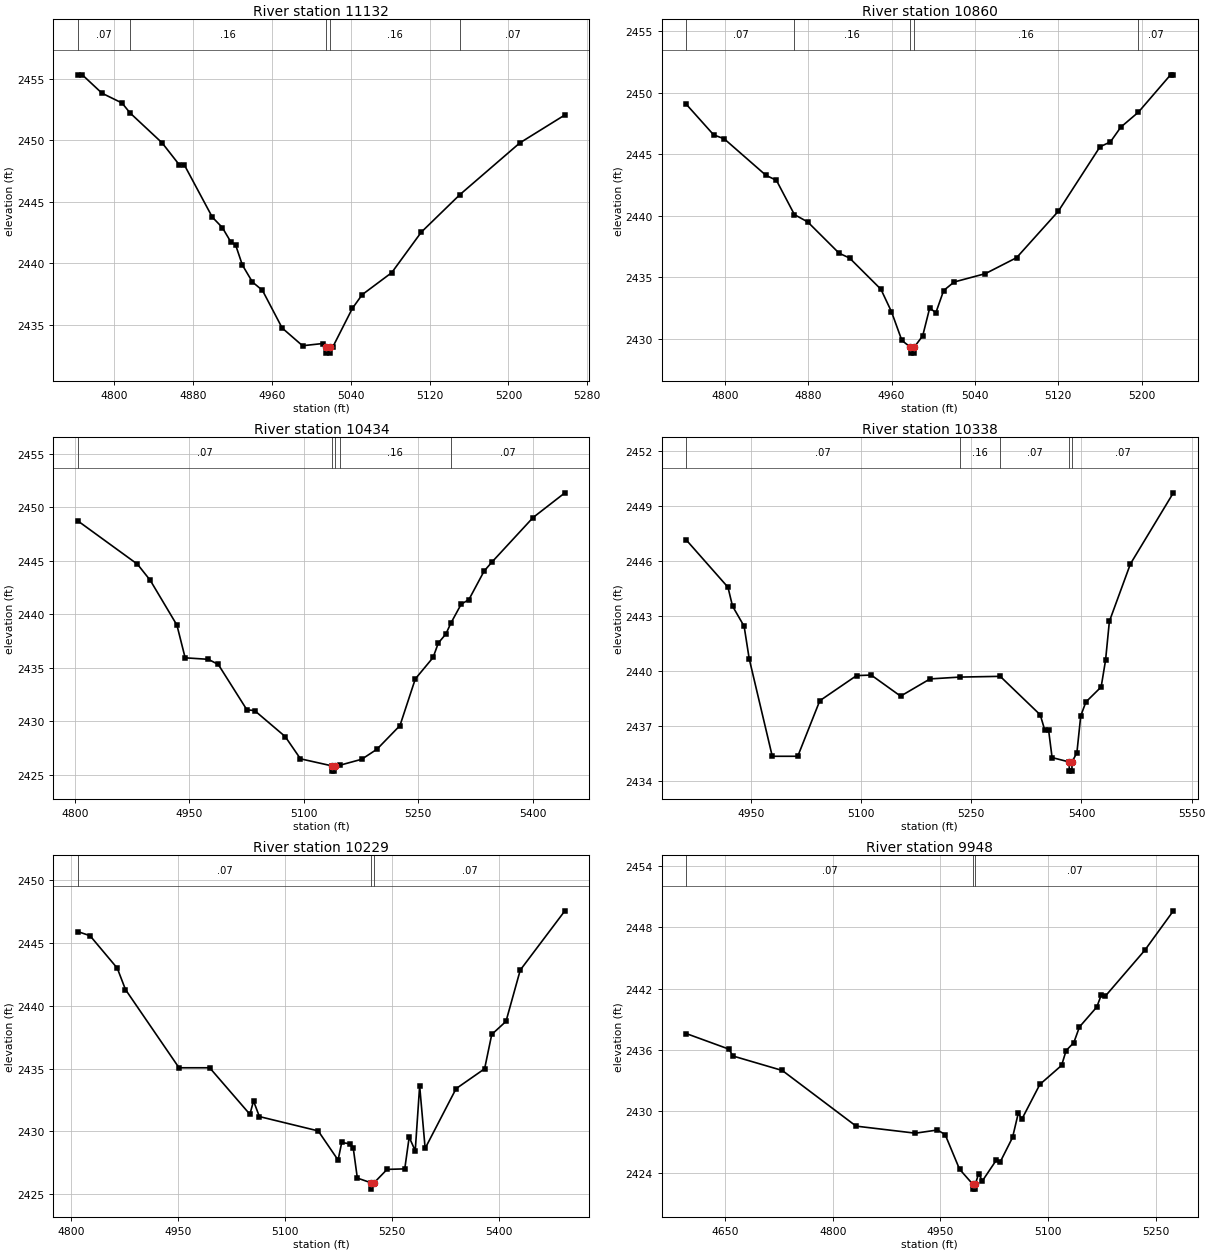
Type RM Length L Ch R = 1,11132,272,272,272
BEGIN DESCRIPTION:
182
END DESCRIPTION:
XS GIS Cut Line= 3
      1462920.39      6793022.08      1462967.83      6792772.60
      1462965.97      6792532.26
#Sta/Elev= 30
  4763.0 2455.32  4767.6 2455.32  4787.5 2453.83  4807.9 2453.03  4816.1 2452.22
  4848.6 2449.79  4865.9 2448.02  4871.0 2448.02  4899.5 2443.76  4909.7 2442.91
  4918.1 2441.77  4923.2 2441.49  4930.0 2439.87  4940.2 2438.49  4950.4 2437.81
  4970.4 2434.75  4991.1 2433.31  5011.5 2433.49  5014.7 2433.21  5015.0 2432.71
  5018.5 2432.71  5018.7 2433.21  5021.8 2433.21  5041.6 2436.34  5051.6 2437.46
  5081.6 2439.25  5111.6 2442.54  5150.8 2445.59  5211.6 2449.79  5257.3 2452.06
#Mann=5,-1,0
  4763.0    0.07       0  4816.1    0.16       0  5014.7    0.07       0
  5018.7    0.16       0  5150.8    0.07       0
Bank Sta=5014.7,5018.7
Exp/Cntr=0.3,0.1

Type RM Length L Ch R = 1,10860,426,426,426
BEGIN DESCRIPTION:
181
END DESCRIPTION:
XS GIS Cut Line= 3
      1463191.66      6793024.25      1463210.14      6792787.97
      1463213.36      6792557.60
#Sta/Elev= 30
  4763.0 2449.08  4789.3 2446.59  4799.4 2446.27  4839.5 2443.30  4849.5 2442.90
  4866.8 2440.11  4879.6 2439.51  4909.7 2436.97  4919.7 2436.58  4949.8 2434.04
  4959.9 2432.22  4969.9 2429.88  4977.9 2429.35  4978.2 2428.85  4981.7 2428.85
  4981.9 2429.35  4989.9 2430.26  4996.6 2432.52  5002.5 2432.13  5010.0 2433.94
  5020.0 2434.63  5050.0 2435.31  5080.0 2436.61  5120.0 2440.38  5160.0 2445.62
  5170.0 2446.02  5180.0 2447.22  5196.8 2448.43  5227.7 2451.47  5230.4 2451.47
#Mann=5,-1,0
  4763.0    0.07       0  4866.8    0.16       0  4977.9    0.07       0
  4981.9    0.16       0  5196.8    0.07       0
Bank Sta=4977.9,4981.9
Exp/Cntr=0.3,0.1

Type RM Length L Ch R = 1,10434,96,96,96
BEGIN DESCRIPTION:
745
END DESCRIPTION:
XS GIS Cut Line= 3
      1463525.85      6793093.70      1463571.43      6792917.88
      1463536.74      6792462.53
#Sta/Elev= 30
  4803.8 2448.71  4882.0 2444.66  4898.8 2443.15  4933.7 2438.97  4944.5 2435.91
  4974.8 2435.77  4987.9 2435.29  5025.4 2431.05  5035.5 2430.98  5075.6 2428.55
  5095.6 2426.47  5136.3 2425.82  5136.6 2425.32  5140.1 2425.32  5140.3 2425.82
  5147.2 2425.87  5175.9 2426.43  5195.9 2427.37  5226.0 2429.58  5246.1 2433.94
  5269.4 2435.94  5276.2 2437.29  5286.2 2438.14  5292.6 2439.14  5306.2 2440.92
  5316.3 2441.35  5336.3 2444.02  5346.4 2444.85  5400.4 2449.02  5442.1 2451.33
#Mann=5,-1,0
  4803.8    0.07       0  5136.3    0.07       0  5140.3    0.07       0
  5147.2    0.16       0  5292.6    0.07       0
Bank Sta=5136.3,5140.3
Exp/Cntr=0.3,0.1

Type RM Length L Ch R = 1,10338,109,109,109
BEGIN DESCRIPTION:
180
END DESCRIPTION:
XS GIS Cut Line= 4
      1463573.60      6793093.67      1463638.33      6792971.79
      1463647.39      6792620.57      1463695.12      6792453.50
#Sta/Elev= 30
  4862.0 2447.16  4918.8 2444.58  4925.0 2443.55  4940.8 2442.45  4947.7 2440.68
  4979.1 2435.36  5013.8 2435.36  5043.8 2438.39  5093.8 2439.76  5113.8 2439.79
  5153.8 2438.64  5193.9 2439.58  5234.5 2439.68  5289.4 2439.72  5343.9 2437.62
  5350.1 2436.78  5355.3 2436.78  5360.0 2435.29  5383.2 2435.05  5383.5 2434.55
  5387.0 2434.55  5387.2 2435.05  5393.8 2435.56  5399.0 2437.56  5406.0 2438.32
  5426.8 2439.14  5432.8 2440.60  5438.0 2442.72  5466.6 2445.85  5525.1 2449.73
#Mann=5,-1,0
  4862.0    0.07       0  5234.5    0.16       0  5289.4    0.07       0
  5383.2    0.07       0  5387.2    0.07       0
Bank Sta=5383.2,5387.2
Exp/Cntr=0.3,0.1

Type RM Length L Ch R = 1,10229,281,281,281
BEGIN DESCRIPTION:
744
END DESCRIPTION:
XS GIS Cut Line= 6
      1463671.28      6793137.03      1463721.17      6793043.75
      1463734.19      6792965.62      1463686.45      6792774.65
      1463762.41      6792692.18      1463771.09      6792505.52
#Sta/Elev= 30
  4809.1 2445.89  4826.3 2445.56  4864.5 2442.98  4876.0 2441.28  4951.1 2435.06
  4994.1 2435.06  5050.5 2431.36  5055.6 2432.42  5063.8 2431.18  5146.3 2430.04
  5174.2 2427.72  5179.3 2429.12  5190.9 2429.01  5195.4 2428.70  5201.2 2426.29
  5220.6 2425.91  5220.9 2425.41  5224.6 2425.91  5242.9 2426.98  5267.7 2427.02
  5273.9 2429.54  5282.4 2428.46  5288.6 2433.62  5296.3 2428.65  5339.7 2433.40
  5379.7 2434.98  5389.7 2437.71  5409.7 2438.75  5429.7 2442.83  5492.3 2447.54
#Mann=3,-1,0
  4809.1    0.07       0  5220.6    0.07       0  5224.6    0.07       0
Bank Sta=5220.6,5224.6
Exp/Cntr=0.3,0.1

Type RM Length L Ch R = 1,9948,428,428,428
BEGIN DESCRIPTION:
179
END DESCRIPTION:
XS GIS Cut Line= 3
      1463805.00      6793138.01      1463901.42      6792745.48
      1463805.01      6792488.04
#Sta/Elev= 30
  4595.8 2437.60  4655.6 2436.07  4660.7 2435.41  4729.7 2433.99  4832.6 2428.55
  4915.2 2427.86  4945.9 2428.17  4956.7 2427.73  4976.8 2424.34  4995.0 2422.89
  4995.3 2422.39  4998.8 2422.39  4999.0 2422.89  5003.3 2423.89  5008.7 2423.20
  5028.3 2425.25  5033.6 2425.06  5050.7 2427.44  5058.6 2429.79  5063.9 2429.26
  5088.8 2432.63  5119.1 2434.49  5125.4 2435.94  5136.1 2436.71  5144.0 2438.25
  5168.2 2440.20  5174.3 2441.36  5179.7 2441.23  5234.9 2445.73  5274.9 2449.60
#Mann=3,-1,0
  4595.8    0.07       0  4995.0    0.07       0  4999.0    0.07       0
Bank Sta=4995,4999
Exp/Cntr=0.3,0.1

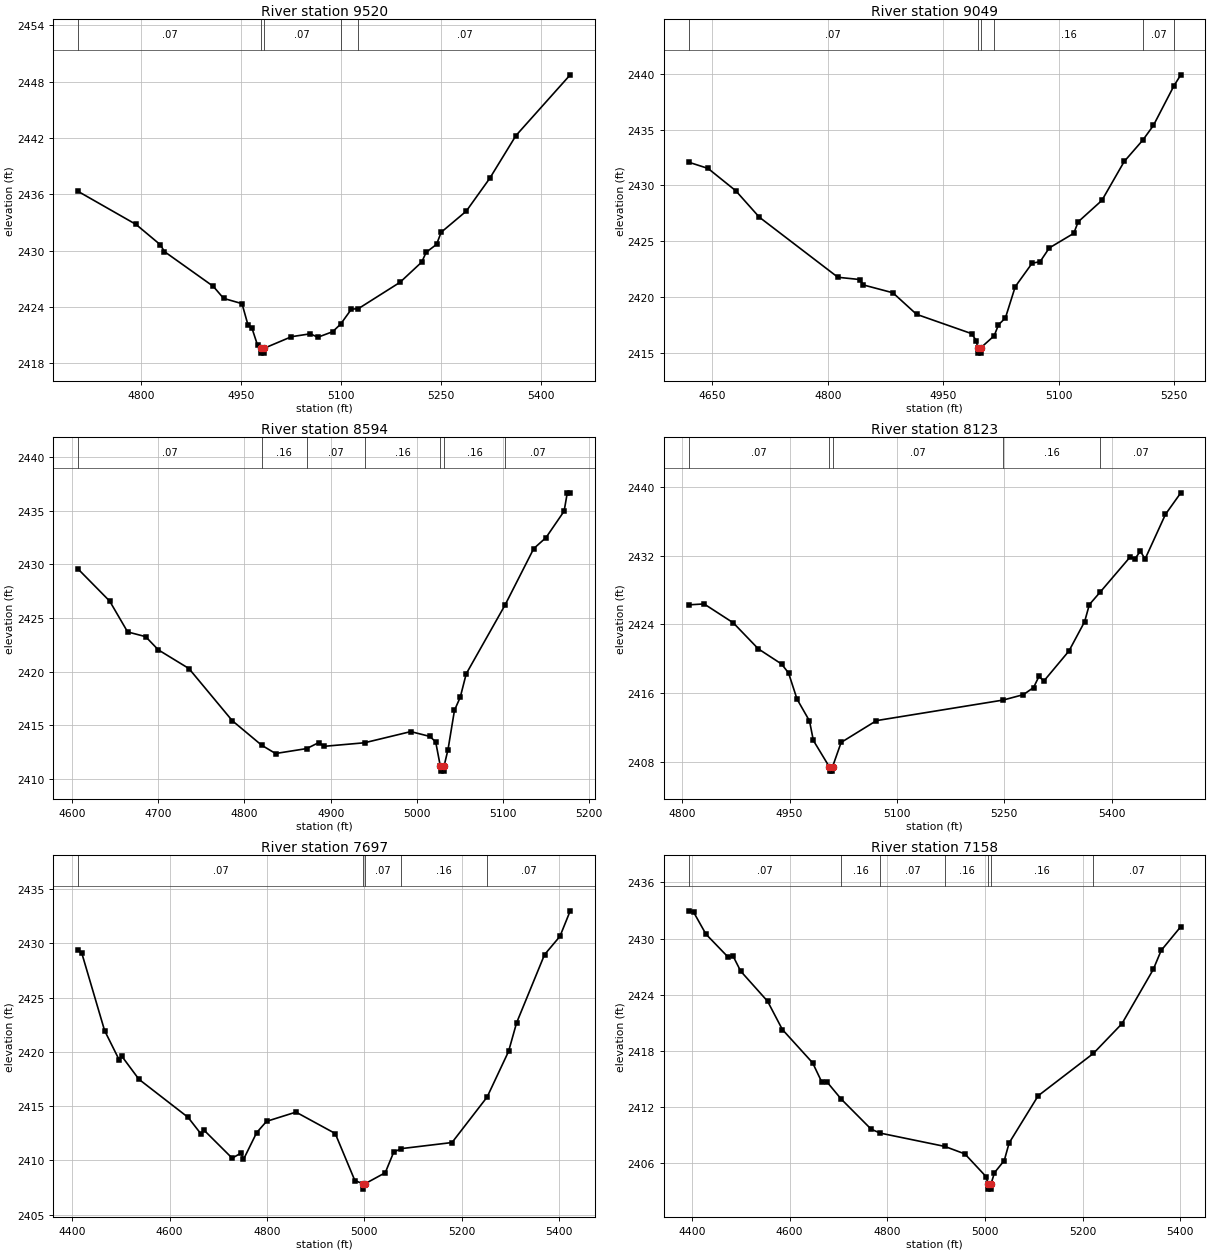
Type RM Length L Ch R = 1,9520,471,471,471
BEGIN DESCRIPTION:
178
END DESCRIPTION:
XS GIS Cut Line= 3
      1464404.99      6793087.98      1464251.16      6792836.61
      1464054.98      6792437.97
#Sta/Elev= 30
  4705.3 2436.31  4792.3 2432.79  4829.1 2430.61  4834.9 2429.90  4908.4 2426.19
  4923.9 2424.91  4951.5 2424.35  4960.6 2422.05  4966.5 2421.73  4974.9 2419.91
  4979.8 2419.58  4980.1 2419.08  4983.8 2419.08  4984.1 2419.58  5025.8 2420.83
  5054.2 2421.14  5065.2 2420.77  5087.6 2421.36  5099.6 2422.17  5115.7 2423.76
  5126.3 2423.82  5188.7 2426.62  5221.4 2428.78  5228.0 2429.82  5243.6 2430.66
  5250.5 2431.95  5288.2 2434.20  5323.5 2437.70  5362.8 2442.25  5444.3 2448.72
#Mann=5,-1,0
  4705.3    0.07       0  4979.8    0.07       0  4984.1    0.07       0
  5099.6    0.16       0  5126.3    0.07       0
Bank Sta=4979.8,4984.1
Exp/Cntr=0.3,0.1

Type RM Length L Ch R = 1,9049,455,455,455
BEGIN DESCRIPTION:
177
END DESCRIPTION:
XS GIS Cut Line= 3
      1464604.99      6792887.97      1464528.73      6792514.88
      1464405.01      6792288.03
#Sta/Elev= 30
  4619.2 2432.08  4644.4 2431.52  4680.4 2429.52  4711.0 2427.15  4813.1 2421.76
  4841.2 2421.56  4846.3 2421.07  4884.5 2420.37  4915.2 2418.44  4986.6 2416.71
  4992.7 2416.09  4994.6 2415.46  4994.9 2414.96  4998.7 2414.96  4999.0 2415.46
  5016.1 2416.52  5021.6 2417.50  5030.6 2418.11  5043.4 2420.92  5065.3 2423.02
  5075.7 2423.16  5087.6 2424.39  5119.4 2425.70  5125.1 2426.73  5155.9 2428.65
  5184.9 2432.14  5209.1 2434.06  5222.8 2435.37  5249.6 2438.94  5258.4 2439.91
#Mann=6,-1,0
  4619.2    0.07       0  4994.6    0.07       0  4999.0    0.07       0
  5016.1    0.16       0  5209.1    0.07       0  5249.6    0.16       0
Bank Sta=4994.6,4999
Exp/Cntr=0.3,0.1

Type RM Length L Ch R = 1,8594,471,471,471
BEGIN DESCRIPTION:
176
END DESCRIPTION:
XS GIS Cut Line= 3
      1465105.00      6792388.00      1464787.69      6792156.29
      1464654.97      6792037.98
#Sta/Elev= 30
  4607.1 2429.56  4643.8 2426.57  4664.6 2423.70  4685.5 2423.26  4700.2 2422.03
  4735.7 2420.29  4785.9 2415.44  4819.9 2413.16  4836.1 2412.38  4872.3 2412.84
  4886.3 2413.40  4892.5 2413.05  4939.3 2413.38  4992.9 2414.42  5015.1 2413.97
  5021.8 2413.46  5027.1 2411.24  5027.4 2410.74  5031.3 2410.74  5031.6 2411.24
  5036.1 2412.75  5043.6 2416.41  5050.3 2417.62  5057.2 2419.80  5102.2 2426.20
  5135.5 2431.46  5149.7 2432.48  5170.7 2434.94  5174.4 2436.65  5177.8 2436.65
#Mann=7,-1,0
  4607.1    0.07       0  4819.9    0.16       0  4872.3    0.07       0
  4939.3    0.16       0  5027.1    0.07       0  5031.6    0.16       0
  5102.2    0.07       0
Bank Sta=5027.1,5031.6
Exp/Cntr=0.3,0.1

Type RM Length L Ch R = 1,8123,426,426,426
BEGIN DESCRIPTION:
175
END DESCRIPTION:
XS GIS Cut Line= 3
      1465204.99      6792287.97      1465131.99      6792111.47
      1464755.04      6791788.03
#Sta/Elev= 30
  4809.0 2426.26  4830.6 2426.37  4871.4 2424.17  4906.4 2421.14  4938.8 2419.38
  4948.6 2418.34  4960.5 2415.29  4977.9 2412.75  4983.3 2410.48  5005.6 2407.41
  5005.9 2406.91  5009.8 2406.91  5010.1 2407.41  5022.1 2410.25  5071.5 2412.79
  5248.4 2415.18  5276.7 2415.81  5291.0 2416.64  5298.6 2417.95  5305.2 2417.38
  5340.4 2420.89  5362.3 2424.30  5368.9 2426.29  5384.3 2427.77  5426.0 2431.84
  5432.5 2431.61  5440.2 2432.50  5446.8 2431.60  5475.3 2436.80  5496.7 2439.30
#Mann=5,-1,0
  4809.0    0.07       0  5005.6    0.07       0  5010.1    0.07       0
  5248.4    0.16       0  5384.3    0.07       0
Bank Sta=5005.6,5010.1
Exp/Cntr=0.3,0.1

Type RM Length L Ch R = 1,7697,539,539,539
BEGIN DESCRIPTION:
174
END DESCRIPTION:
XS GIS Cut Line= 3
      1465839.23      6791793.75      1465255.53      6791722.81
      1464855.01      6791588.00
#Sta/Elev= 30
  4412.0 2429.36  4419.7 2429.09  4466.6 2421.95  4496.5 2419.26  4501.5 2419.62
  4537.1 2417.47  4637.9 2413.97  4665.0 2412.41  4670.0 2412.82  4728.5 2410.21
  4746.7 2410.68  4751.7 2410.09  4778.9 2412.57  4799.1 2413.60  4859.5 2414.45
  4940.1 2412.48  4980.4 2408.15  4996.9 2407.86  4997.3 2407.36  5001.5 2407.86
  5042.8 2408.87  5060.3 2410.78  5076.0 2411.09  5179.9 2411.65  5252.0 2415.84
  5296.0 2420.04  5312.4 2422.66  5369.9 2428.95  5401.5 2430.63  5422.6 2432.98
#Mann=5,-1,0
  4412.0    0.07       0  4996.9    0.07       0  5001.5    0.07       0
  5076.0    0.16       0  5252.0    0.07       0
Bank Sta=4996.9,5001.5
Exp/Cntr=0.3,0.1

Type RM Length L Ch R = 1,7158,494,494,494
BEGIN DESCRIPTION:
173
END DESCRIPTION:
XS GIS Cut Line= 3
      1465854.97      6791338.00      1465254.34      6791253.16
      1464854.95      6791288.00
#Sta/Elev= 30
  4393.4 2432.96  4403.5 2432.83  4428.9 2430.47  4474.2 2428.02  4484.3 2428.14
  4500.0 2426.52  4555.0 2423.31  4585.3 2420.29  4647.3 2416.73  4666.1 2414.67
  4676.2 2414.72  4705.8 2412.86  4767.0 2409.65  4785.6 2409.23  4917.7 2407.81
  4958.9 2407.01  5002.2 2404.59  5006.6 2403.75  5007.0 2403.25  5011.7 2403.25
  5012.2 2403.75  5019.4 2405.00  5039.5 2406.30  5049.5 2408.18  5109.0 2413.22
  5222.0 2417.74  5280.4 2420.91  5344.5 2426.70  5360.7 2428.73  5400.9 2431.27
#Mann=7,-1,0
  4393.4    0.07       0  4705.8    0.16       0  4785.6    0.07       0
  4917.7    0.16       0  5006.6    0.07       0  5012.2    0.16       0
  5222.0    0.07       0
Bank Sta=5006.6,5012.2
Exp/Cntr=0.3,0.1

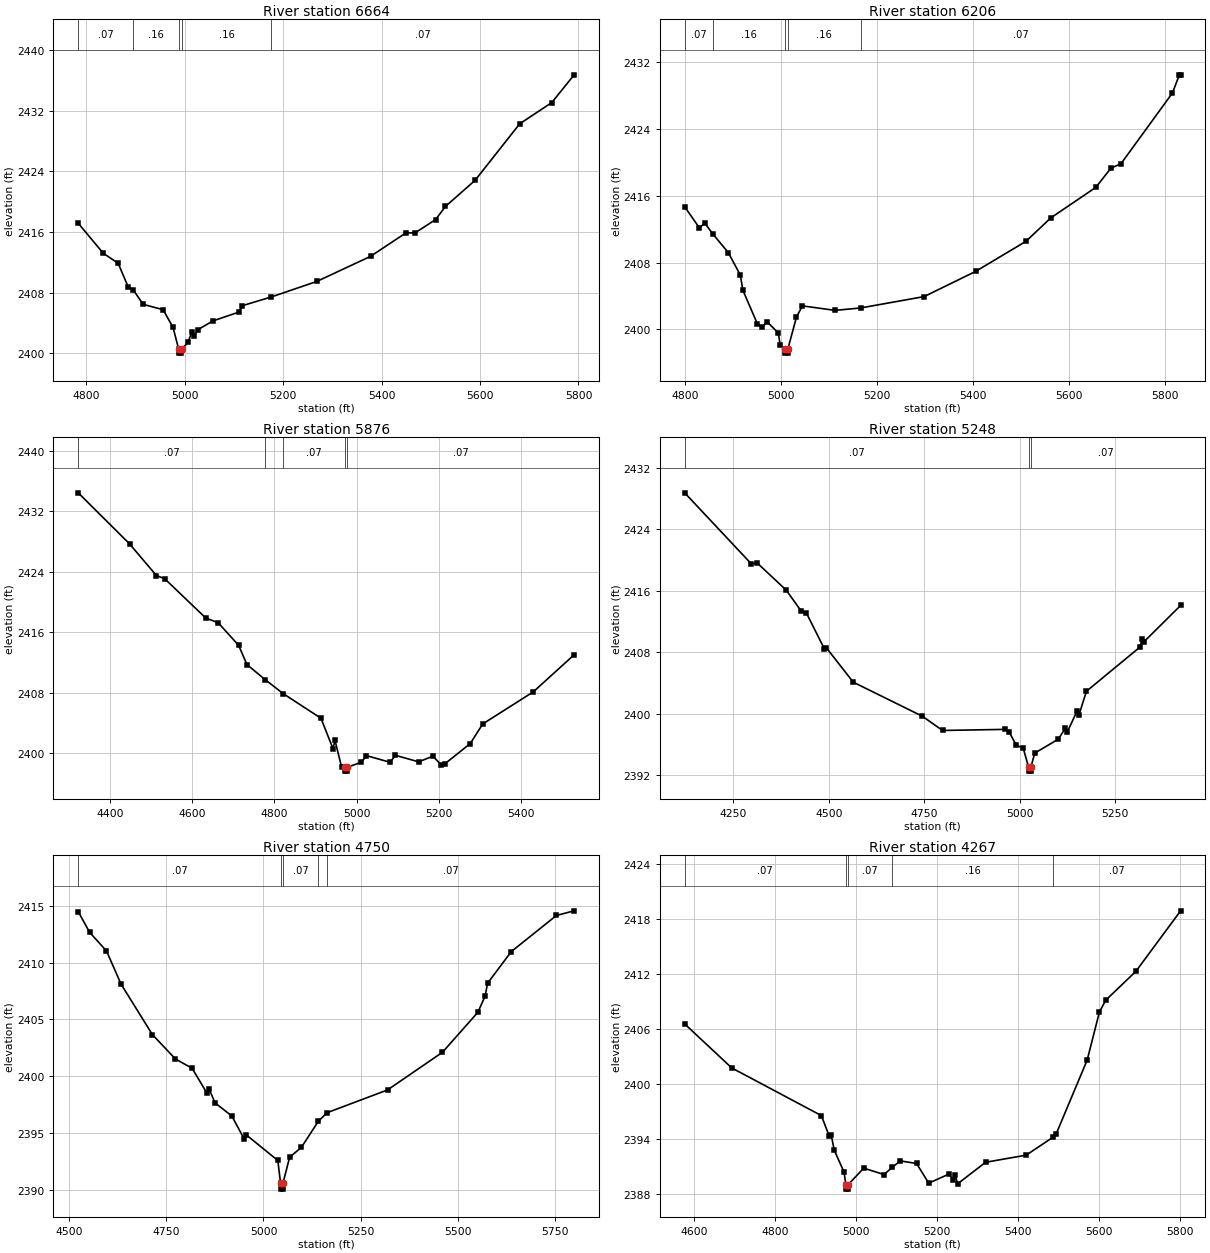
Type RM Length L Ch R = 1,6664,458,458,458
BEGIN DESCRIPTION:
172
END DESCRIPTION:
XS GIS Cut Line= 3
      1465705.04      6790938.01      1465491.38      6790901.22
      1464704.96      6790988.00
#Sta/Elev= 30
  4783.2 2417.15  4834.0 2413.20  4864.4 2411.87  4884.7 2408.76  4894.6 2408.40
  4915.2 2406.45  4955.7 2405.75  4976.0 2403.40  4987.5 2400.52  4988.0 2400.02
  4992.8 2400.02  4993.2 2400.52  5006.4 2401.43  5013.9 2402.77  5018.9 2402.29
  5026.5 2403.11  5056.7 2404.26  5109.7 2405.43  5117.1 2406.28  5175.8 2407.43
  5268.0 2409.47  5377.3 2412.78  5449.1 2415.87  5468.1 2415.89  5509.5 2417.63
  5529.6 2419.36  5589.9 2422.81  5680.5 2430.26  5745.7 2433.06  5791.2 2436.72
#Mann=5,-1,0
  4783.2    0.07       0  4894.6    0.16       0  4987.5    0.07       0
  4993.2    0.16       0  5175.8    0.07       0
Bank Sta=4987.5,4993.2
Exp/Cntr=0.3,0.1

Type RM Length L Ch R = 1,6206,330,330,330
BEGIN DESCRIPTION:
171
END DESCRIPTION:
XS GIS Cut Line= 3
      1465755.04      6790488.01      1465555.43      6790461.96
      1464755.04      6790687.99
#Sta/Elev= 30
  4798.7 2414.68  4829.0 2412.18  4840.8 2412.70  4857.1 2411.44  4889.5 2409.19
  4914.7 2406.49  4919.8 2404.70  4950.0 2400.67  4960.1 2400.25  4970.2 2400.92
  4993.7 2399.56  4997.7 2398.10  5007.9 2397.65  5008.4 2397.15  5013.2 2397.15
  5013.7 2397.65  5031.6 2401.48  5043.9 2402.81  5111.9 2402.27  5165.3 2402.56
  5297.4 2403.92  5404.5 2406.93  5509.6 2410.54  5561.6 2413.36  5655.1 2417.00
  5686.3 2419.29  5707.6 2419.84  5814.7 2428.31  5829.1 2430.48  5831.7 2430.48
#Mann=5,-1,0
  4798.7    0.07       0  4857.1    0.16       0  5007.9    0.07       0
  5013.7    0.16       0  5165.3    0.07       0
Bank Sta=5007.9,5013.7
Exp/Cntr=0.3,0.1

Type RM Length L Ch R = 1,5876,628,628,628
BEGIN DESCRIPTION:
170
END DESCRIPTION:
XS GIS Cut Line= 3
      1466155.03      6790188.00      1465478.58      6790160.85
      1464955.03      6790238.00
#Sta/Elev= 30
  4323.0 2434.46  4447.9 2427.70  4513.2 2423.50  4533.2 2423.09  4633.3 2417.87
  4663.3 2417.26  4713.3 2414.25  4733.4 2411.71  4777.7 2409.72  4821.4 2407.87
  4913.5 2404.60  4942.5 2400.59  4947.5 2401.67  4963.5 2398.15  4970.7 2398.10
  4971.1 2397.60  4976.0 2397.60  4976.5 2398.10  5011.7 2398.77  5023.8 2399.66
  5081.4 2398.77  5094.6 2399.69  5151.1 2398.83  5185.6 2399.58  5205.8 2398.45
  5215.7 2398.61  5276.5 2401.25  5306.9 2403.85  5429.8 2408.10  5529.2 2413.01
#Mann=5,-1,0
  4323.0    0.07       0  4777.7    0.16       0  4821.4    0.07       0
  4970.7    0.07       0  4976.5    0.07       0
Bank Sta=4970.7,4976.5
Exp/Cntr=0.3,0.1

Type RM Length L Ch R = 1,5248,498,498,498
BEGIN DESCRIPTION:
169
END DESCRIPTION:
XS GIS Cut Line= 3
      1466055.02      6790138.01      1465249.35      6789790.29
      1464855.01      6789938.00
#Sta/Elev= 30
  4122.5 2428.76  4296.8 2419.53  4312.5 2419.63  4388.4 2416.10  4427.5 2413.39
  4440.9 2413.16  4487.9 2408.50  4493.4 2408.61  4563.9 2404.13  4744.8 2399.70
  4797.8 2397.85  4961.2 2397.99  4972.7 2397.60  4990.8 2395.92  5008.9 2395.56
  5023.1 2393.06  5023.6 2392.56  5028.5 2392.56  5029.0 2393.06  5039.1 2394.90
  5100.8 2396.72  5119.3 2398.14  5124.6 2397.68  5149.5 2400.33  5154.9 2399.87
  5174.5 2402.95  5314.3 2408.68  5320.5 2409.78  5325.8 2409.42  5421.1 2414.11
#Mann=3,-1,0
  4122.5    0.07       0  5023.1    0.07       0  5029.0    0.07       0
Bank Sta=5023.1,5029
Exp/Cntr=0.3,0.1

Type RM Length L Ch R = 1,4750,483,483,483
BEGIN DESCRIPTION:
168
END DESCRIPTION:
XS GIS Cut Line= 4
      1465855.00      6789688.00      1465441.53      6789451.57
      1465209.59      6789483.46      1464680.34      6789680.04
#Sta/Elev= 30
  4523.7 2414.48  4553.2 2412.65  4596.4 2411.02  4633.8 2408.10  4714.4 2403.66
  4773.4 2401.52  4816.6 2400.69  4854.1 2398.54  4859.8 2398.89  4875.6 2397.65
  4918.8 2396.49  4949.9 2394.50  4956.3 2394.82  5036.9 2392.58  5044.0 2390.56
  5044.5 2390.06  5049.5 2390.06  5050.0 2390.56  5067.2 2392.87  5097.4 2393.73
  5141.2 2396.04  5163.2 2396.78  5319.0 2398.79  5460.1 2402.10  5551.2 2405.62
  5569.7 2407.04  5576.2 2408.18  5637.0 2410.96  5753.1 2414.14  5798.7 2414.55
#Mann=5,-1,0
  4523.7    0.07       0  5044.0    0.07       0  5050.0    0.07       0
  5141.2    0.16       0  5163.2    0.07       0
Bank Sta=5044,5050
Exp/Cntr=0.3,0.1

Type RM Length L Ch R = 1,4267,890,890,890
BEGIN DESCRIPTION:
167
END DESCRIPTION:
XS GIS Cut Line= 3
      1465855.02      6789138.01      1465454.66      6789003.04
      1464655.00      6788938.00
#Sta/Elev= 30
  4577.5 2406.53  4693.6 2401.73  4915.2 2396.52  4934.3 2394.30  4939.6 2394.36
  4946.9 2392.74  4971.0 2390.37  4975.5 2389.00  4976.0 2388.50  4981.0 2388.50
  4981.5 2389.00  5019.7 2390.79  5069.9 2390.09  5090.1 2390.88  5110.0 2391.58
  5150.1 2391.30  5180.2 2389.15  5230.4 2390.15  5240.4 2389.49  5246.3 2390.02
  5251.3 2389.07  5320.7 2391.43  5421.0 2392.21  5486.7 2394.15  5495.1 2394.54
  5571.5 2402.58  5601.6 2407.80  5617.0 2409.10  5691.9 2412.27  5802.3 2418.87
#Mann=5,-1,0
  4577.5    0.07       0  4975.5    0.07       0  4981.5    0.07       0
  5090.1    0.16       0  5486.7    0.07       0
Bank Sta=4975.5,4981.5
Exp/Cntr=0.3,0.1

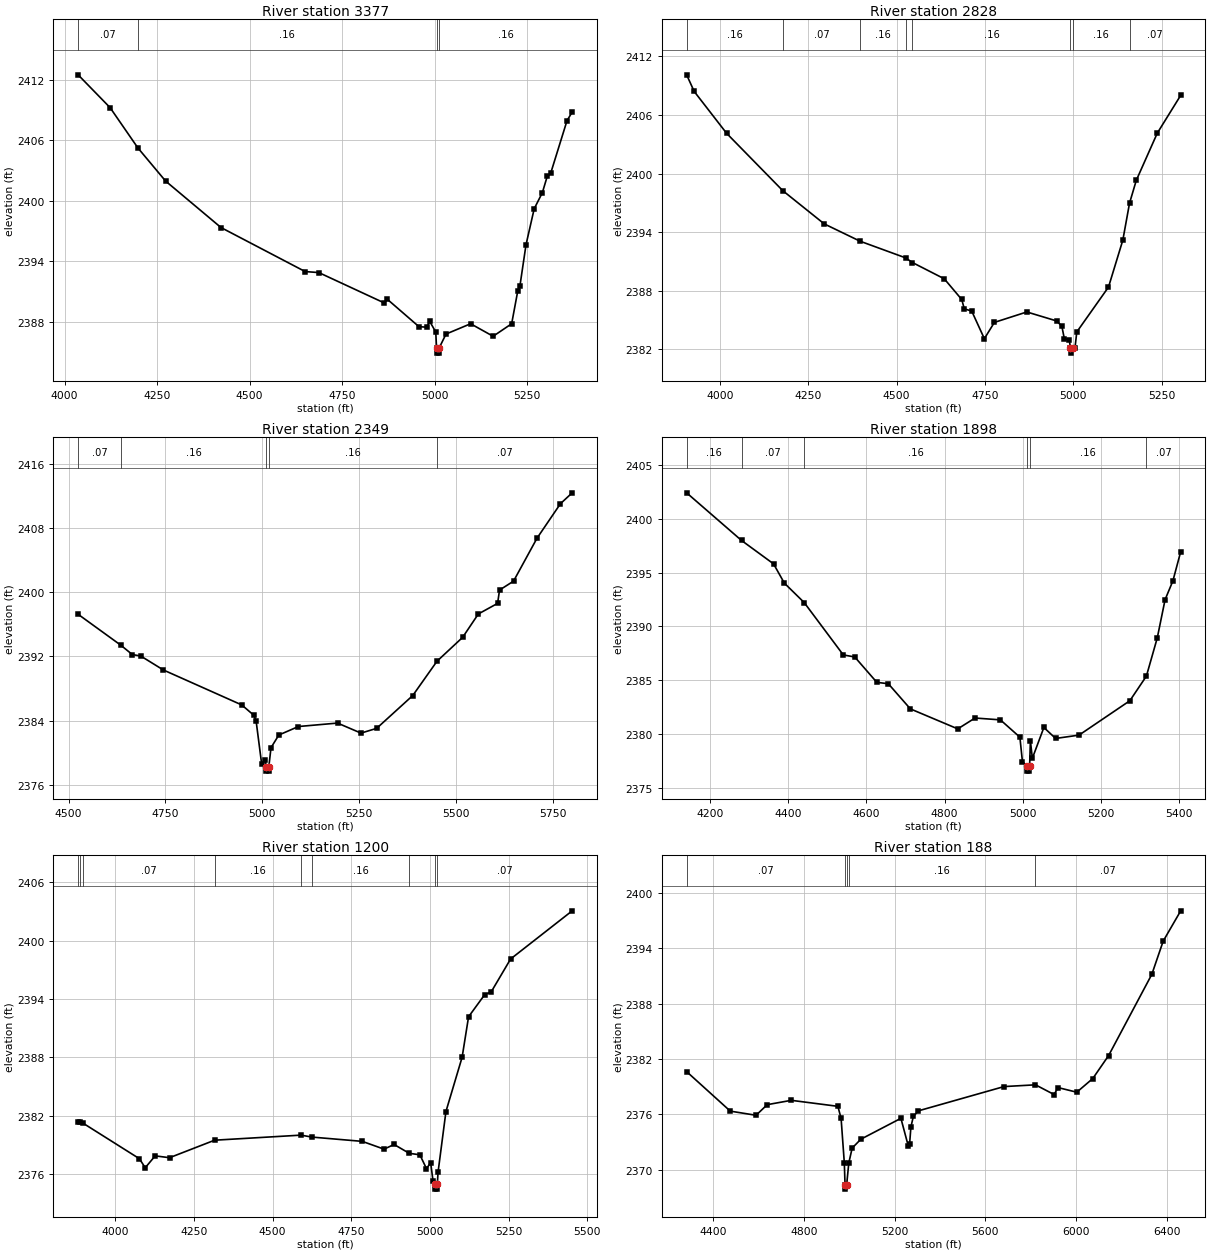
Type RM Length L Ch R = 1,3377,549,549,549
BEGIN DESCRIPTION:
166
END DESCRIPTION:
XS GIS Cut Line= 3
      1466054.99      6788987.99      1465285.71      6788408.03
      1464954.96      6788237.98
#Sta/Elev= 30
  4036.6 2412.47  4123.0 2409.22  4198.3 2405.22  4272.9 2401.95  4422.8 2397.34
  4650.2 2392.98  4687.1 2392.88  4864.1 2389.87  4872.4 2390.23  4957.8 2387.52
  4978.6 2387.47  4986.9 2388.04  5003.2 2386.99  5005.3 2385.40  5005.8 2384.90
  5011.7 2384.90  5012.2 2385.40  5030.9 2386.79  5097.4 2387.81  5158.2 2386.57
  5208.3 2387.81  5224.9 2391.08  5230.5 2391.52  5247.1 2395.64  5269.2 2399.20
  5291.4 2400.81  5304.4 2402.41  5313.6 2402.70  5358.0 2407.94  5371.9 2408.78
#Mann=4,-1,0
  4036.6    0.07       0  4198.3    0.16       0  5005.3    0.07       0
  5012.2    0.16       0
Bank Sta=5005.3,5012.2
Exp/Cntr=0.3,0.1

Type RM Length L Ch R = 1,2828,479,479,479
BEGIN DESCRIPTION:
165
END DESCRIPTION:
XS GIS Cut Line= 3
      1466105.03      6788738.03      1465302.81      6787994.05
      1465003.75      6787941.75
#Sta/Elev= 30
  3905.9 2410.12  3927.2 2408.42  4019.1 2404.12  4178.0 2398.24  4295.1 2394.84
  4396.8 2393.06  4525.1 2391.36  4544.5 2390.88  4634.7 2389.21  4684.1 2387.09
  4691.4 2386.13  4712.4 2385.90  4748.1 2383.07  4776.5 2384.74  4868.3 2385.81
  4953.4 2384.88  4967.5 2384.32  4974.3 2383.08  4988.5 2382.92  4991.6 2382.09
  4992.1 2381.59  4998.6 2382.09  5004.5 2382.12  5009.6 2383.76  5099.3 2388.36
  5139.9 2393.18  5158.8 2396.96  5177.9 2399.30  5237.3 2404.14  5303.6 2408.02
#Mann=8,-1,0
  3905.9    0.16       0  4178.0    0.07       0  4396.8    0.16       0
  4525.1    0.07       0  4544.5    0.16       0  4991.6    0.07       0
  4998.6    0.16       0  5158.8    0.07       0
Bank Sta=4991.6,4998.6
Exp/Cntr=0.3,0.1

Type RM Length L Ch R = 1,2349,451,451,451
BEGIN DESCRIPTION:
164
END DESCRIPTION:
XS GIS Cut Line= 3
      1466105.01      6788088.01      1465697.14      6787844.17
      1464905.02      6787738.00
#Sta/Elev= 30
  4524.8 2397.24  4635.1 2393.38  4664.6 2392.22  4686.3 2392.04  4744.6 2390.30
  4946.9 2385.94  4978.1 2384.65  4983.9 2383.95  4998.3 2378.55  5008.0 2379.13
  5009.6 2378.19  5010.1 2377.69  5016.1 2377.69  5016.6 2378.19  5022.3 2380.61
  5042.5 2382.19  5093.0 2383.25  5193.9 2383.68  5254.4 2382.43  5294.8 2383.02
  5387.9 2387.11  5450.5 2391.39  5516.7 2394.37  5557.1 2397.28  5606.8 2398.60
  5611.8 2400.26  5647.9 2401.37  5708.4 2406.72  5769.0 2411.03  5799.2 2412.38
#Mann=5,-1,0
  4524.8    0.07       0  4635.1    0.16       0  5009.6    0.07       0
  5016.6    0.16       0  5450.5    0.07       0
Bank Sta=5009.6,5016.6
Exp/Cntr=0.3,0.1

Type RM Length L Ch R = 1,1898,698,698,698
BEGIN DESCRIPTION:
163
END DESCRIPTION:
XS GIS Cut Line= 3
      1466404.97      6787987.97      1465709.02      6787482.74
      1465304.96      6787488.00
#Sta/Elev= 30
  4140.0 2402.42  4280.4 2397.99  4362.4 2395.81  4390.0 2394.02  4440.8 2392.21
  4540.8 2387.34  4570.1 2387.15  4626.6 2384.79  4656.0 2384.66  4712.4 2382.32
  4833.7 2380.46  4877.8 2381.47  4942.7 2381.30  4992.6 2379.69  4999.2 2377.40
  5010.5 2377.03  5011.0 2376.53  5017.1 2376.53  5017.6 2377.03  5019.5 2379.37
  5024.5 2377.72  5054.0 2380.59  5084.0 2379.57  5144.0 2379.88  5274.0 2383.08
  5316.3 2385.37  5344.1 2388.92  5364.1 2392.48  5384.1 2394.23  5404.1 2396.95
#Mann=6,-1,0
  4140.0    0.16       0  4280.4    0.07       0  4440.8    0.16       0
  5010.5    0.07       0  5017.6    0.16       0  5316.3    0.07       0
Bank Sta=5010.5,5017.6
Exp/Cntr=0.3,0.1

Type RM Length L Ch R = 1,1200,1012,1012,1012
BEGIN DESCRIPTION:
742
END DESCRIPTION:
XS GIS Cut Line= 3
      1466467.88      6787462.20      1465404.63      6787116.95
      1464964.63      6787221.26
#Sta/Elev= 30
  3882.1 2381.36  3886.9 2381.33  3896.7 2381.25  4076.7 2377.58  4095.4 2376.65
  4127.0 2377.87  4172.6 2377.68  4315.9 2379.48  4590.2 2380.00  4625.2 2379.80
  4785.1 2379.36  4854.3 2378.56  4886.2 2379.04  4934.5 2378.13  4968.1 2377.98
  4989.1 2376.56  5002.4 2377.17  5009.9 2375.30  5016.6 2374.95  5017.1 2374.45
  5023.2 2374.45  5023.7 2374.95  5025.8 2376.16  5051.0 2382.43  5102.4 2388.01
  5122.9 2392.17  5174.3 2394.45  5194.7 2394.72  5256.5 2398.11  5452.2 2403.06
#Mann=9,-1,0
  3882.1    0.07       0  3886.9    0.16       0  3896.7    0.07       0
  4315.9    0.16       0  4590.2    0.07       0  4625.2    0.16       0
  4934.5    0.07       0  5016.6    0.07       0  5023.7    0.07       0
Bank Sta=5016.6,5023.7
Exp/Cntr=0.3,0.1

Type RM Length L Ch R = 1,188,0,0,0
BEGIN DESCRIPTION:
743
END DESCRIPTION:
XS GIS Cut Line= 4
      1466489.47      6787415.44      1466006.00      6786887.04
      1465611.99      6786680.02      1464597.99      6786750.01
#Sta/Elev= 30
  4283.8 2380.62  4476.2 2376.34  4589.7 2375.89  4639.0 2377.04  4745.1 2377.51
  4950.4 2376.86  4964.6 2375.55  4978.8 2370.73  4981.9 2368.39  4982.4 2367.89
  4989.2 2368.39  4998.5 2370.72  5013.4 2372.34  5051.8 2373.30  5228.2 2375.56
  5260.9 2372.55  5266.6 2372.78  5272.3 2374.63  5283.0 2375.76  5305.1 2376.37
  5682.6 2379.00  5821.4 2379.19  5903.2 2378.14  5921.1 2378.89  6003.4 2378.39
  6073.9 2379.87  6143.7 2382.36  6334.2 2391.16  6384.3 2394.76  6461.5 2398.04
#Mann=5,-1,0
  4283.8    0.07       0  4981.9    0.07       0  4989.2    0.07       0
  4998.5    0.16       0  5821.4    0.07       0
Bank Sta=4981.9,4989.2
Exp/Cntr=0.3,0.1

Chan Stop Cuts=-1