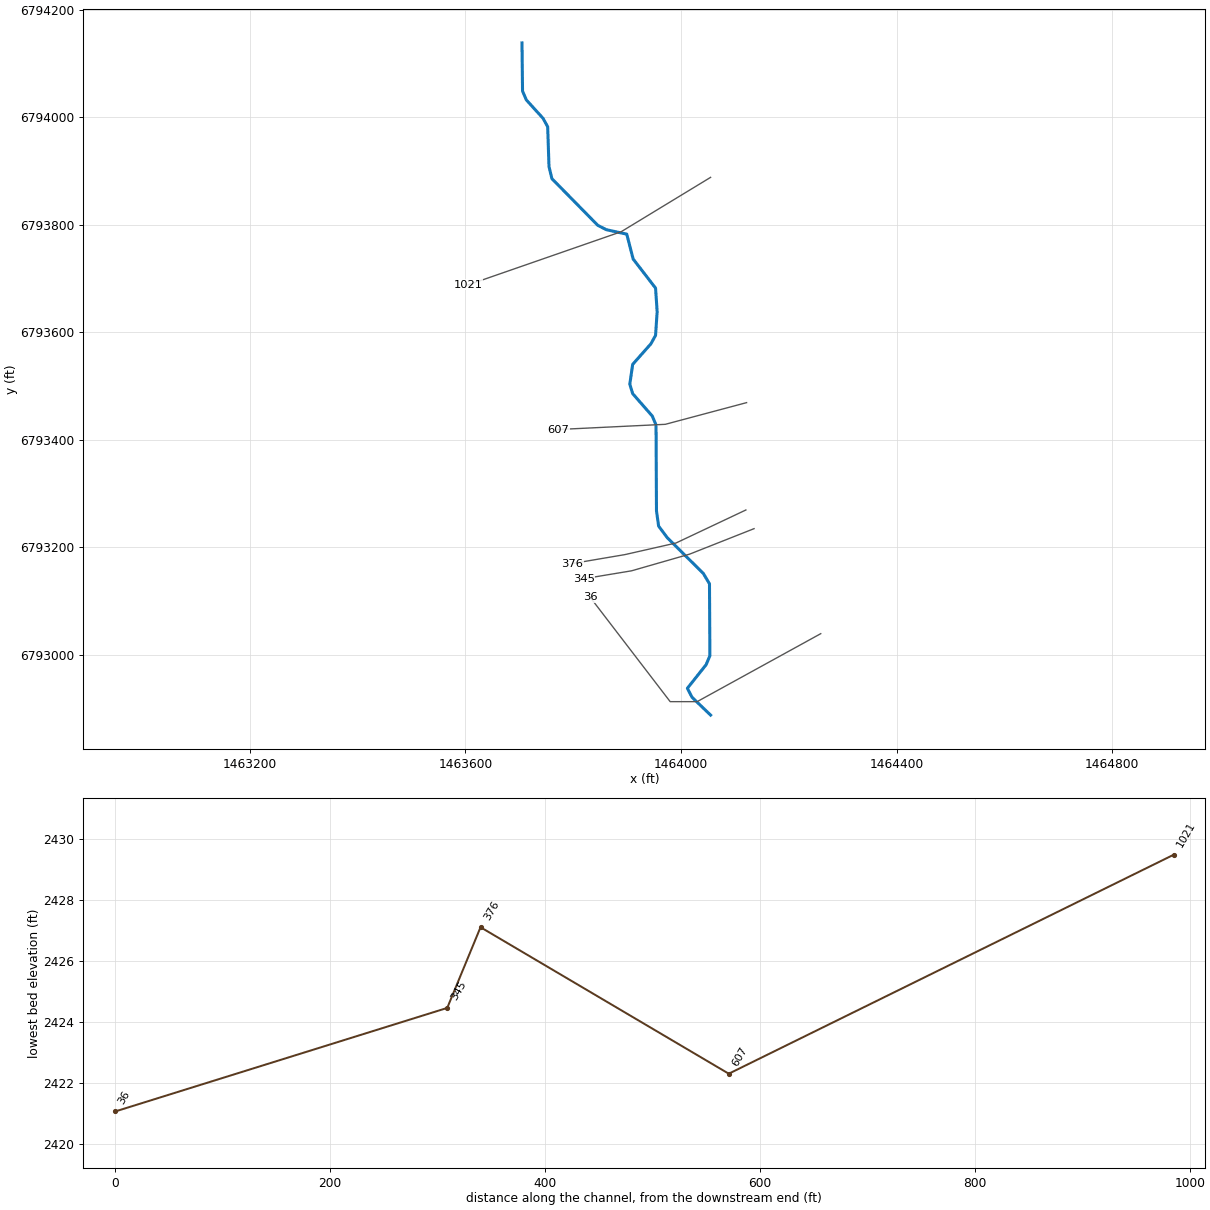
--- Elm 07.prj (project) ---

Proj Title=Elm 07 Base Level Engineering
Current Plan=p01
Default Exp/Contr=0.3,0.1
English Units
Geom File=g01
Flow File=f01
Plan File=p01
BEGIN DESCRIPTION:
Elm 07
END DESCRIPTION:

--- Elm 07.p01 (plan) ---

Plan Title=Multiple Run
Short Identifier=Multiple
Geom File=g01
Flow File=f01
Subcritical Flow
K Sum by GR= 0
Std Step Tol= 0.01
Critical Tol= 0.01
Num of Std Step Trials= 20
Max Error Tol= 0.3
Flow Tol Ratio= 0.001
Split Flow NTrial= 30
Split Flow Tol= 0.02
Split Flow Ratio= 0.02
Log Output Level= 0
Friction Slope Method= 1
Unsteady Friction Slope Method= 2
Unsteady Bridges Friction Slope Method= 1
Parabolic Critical Depth
Global Vel Dist=  1 , 1 , 1
Global Log Level= 0
CheckData=True
Encroach Param= -1, 0, 0, 0
BEGIN DESCRIPTION:
Multiple Run
END DESCRIPTION:

--- Elm 07.f01 (steady flow) ---

Flow Title=Multiple
Number of Profiles=7
Profile Names=10-year,25-year,50-year,1pct_min,100-year,1pct_plu,500-year
River Rch & RM= Elm 07,Reach-1,1021
     148     200     241     180     289     398     421
Boundary for River Rch & Prof#=Elm 07,Reach-1,1
Up Type=0
Dn Type=3
Dn Slope=0.005
Boundary for River Rch & Prof#=Elm 07,Reach-1,2
Up Type=0
Dn Type=3
Dn Slope=0.005
Boundary for River Rch & Prof#=Elm 07,Reach-1,3
Up Type=0
Dn Type=3
Dn Slope=0.005
Boundary for River Rch & Prof#=Elm 07,Reach-1,4
Up Type=0
Dn Type=3
Dn Slope=0.005
Boundary for River Rch & Prof#=Elm 07,Reach-1,5
Up Type=0
Dn Type=3
Dn Slope=0.005
Boundary for River Rch & Prof#=Elm 07,Reach-1,6
Up Type=0
Dn Type=3
Dn Slope=0.005
Boundary for River Rch & Prof#=Elm 07,Reach-1,7
Up Type=0
Dn Type=3
Dn Slope=0.005

--- Elm 07.g01 (geometry) ---

Geom Title=Existing Conditions

River Reach=Elm 07,Reach-1
Reach XY= 30
      1463705.00      6794138.00      1463706.02      6794048.42
      1463713.11      6794031.93      1463744.16      6793997.65
      1463752.66      6793982.03      1463755.12      6793908.05
      1463760.52      6793885.56      1463845.56      6793798.88
      1463861.43      6793790.69      1463899.41      6793782.39
      1463911.28      6793736.16      1463952.87      6793682.06
      1463955.82      6793638.00      1463952.81      6793593.97
      1463944.13      6793578.35      1463910.38      6793540.18
      1463905.09      6793503.39      1463910.38      6793485.82
      1463946.81      6793444.07      1463953.76      6793427.50
      1463954.57      6793267.82      1463958.55      6793239.47
      1463974.65      6793217.85      1464041.60      6793151.30
      1464052.94      6793132.14      1464053.70      6792998.43
      1464046.72      6792981.78      1464011.91      6792937.86
      1464020.54      6792921.16      1464055.00      6792888.00

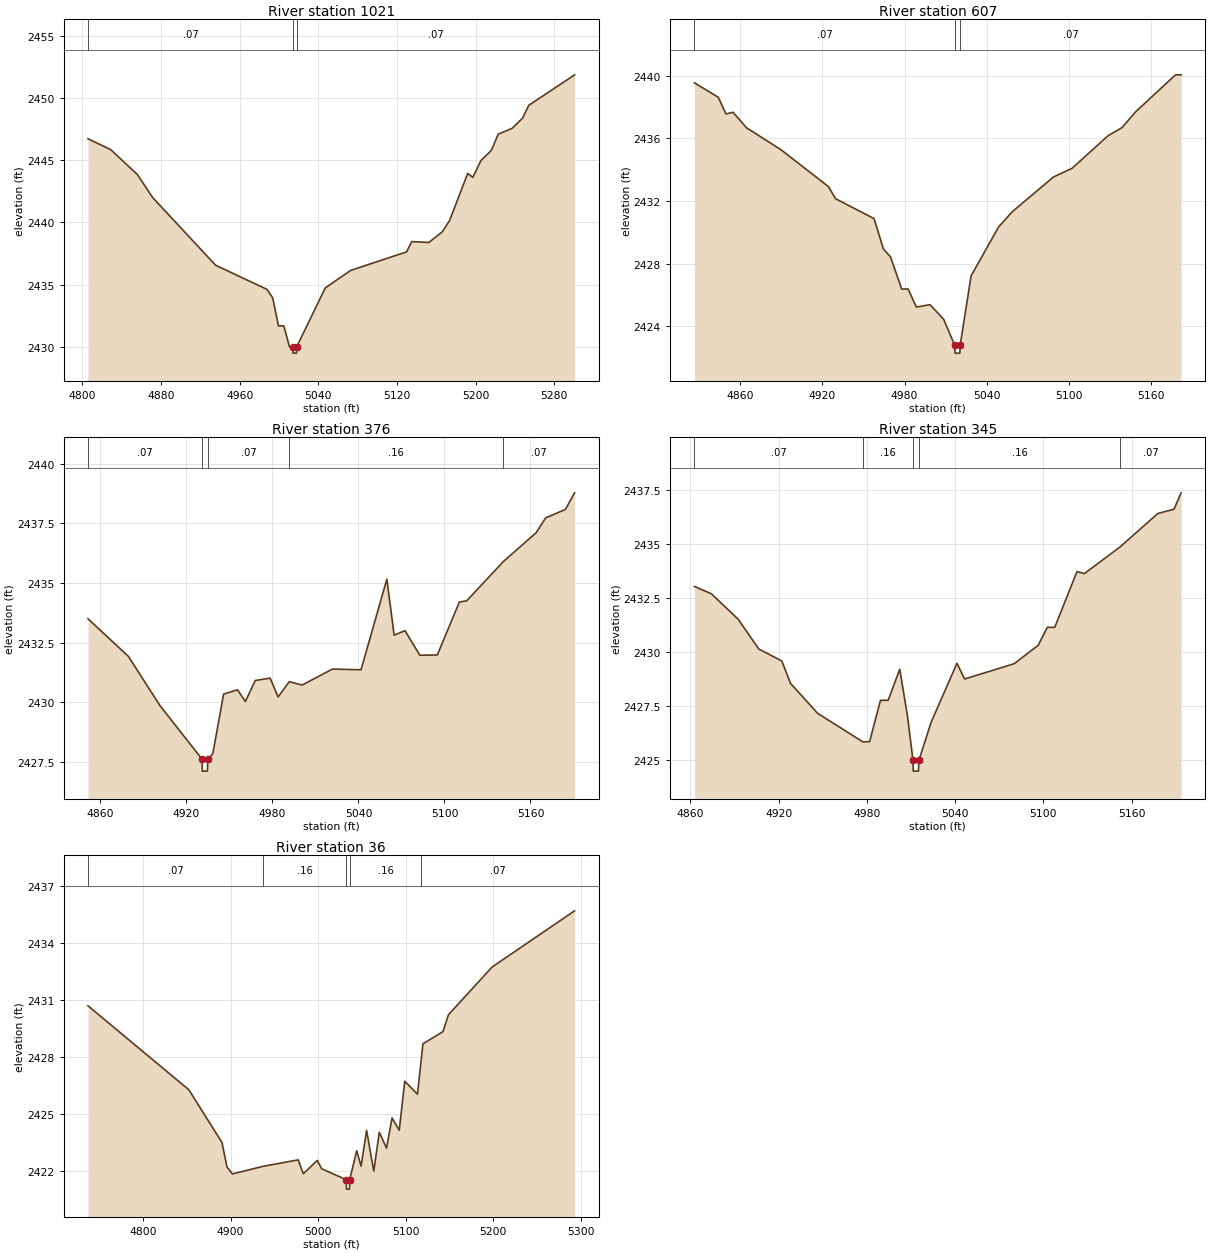
Type RM Length L Ch R = 1,1021,414,414,414
BEGIN DESCRIPTION:
444
END DESCRIPTION:
XS GIS Cut Line= 3
      1464054.99      6793888.00      1463888.98      6793786.85
      1463604.99      6793688.00
#Sta/Elev= 30
  4805.6 2446.73  4828.8 2445.85  4856.0 2443.84  4871.4 2442.00  4935.4 2436.56
  4987.6 2434.62  4993.5 2433.94  4999.4 2431.68  5004.8 2431.68  5010.6 2430.00
  5013.9 2429.99  5014.2 2429.49  5017.7 2429.49  5017.9 2429.99  5047.0 2434.73
  5072.8 2436.14  5129.7 2437.63  5135.0 2438.46  5152.4 2438.39  5166.1 2439.25
  5173.6 2440.17  5191.9 2443.94  5197.2 2443.63  5205.4 2444.98  5216.0 2445.79
  5223.0 2447.10  5237.2 2447.57  5247.7 2448.38  5254.1 2449.42  5300.7 2451.87
#Mann=3,-1,0
  4805.6    0.07       0  5013.9    0.07       0  5017.9    0.07       0
Bank Sta=5013.9,5017.9
Exp/Cntr=0.3,0.1

Type RM Length L Ch R = 1,607,231,231,231
BEGIN DESCRIPTION:
443
END DESCRIPTION:
XS GIS Cut Line= 3
      1464121.78      6793469.07      1463970.98      6793428.74
      1463771.81      6793419.07
#Sta/Elev= 30
  4826.5 2439.54  4843.9 2438.62  4849.5 2437.56  4854.7 2437.66  4864.6 2436.67
  4889.6 2435.28  4924.4 2432.92  4929.6 2432.15  4957.7 2430.88  4964.5 2428.95
  4969.7 2428.44  4977.9 2426.39  4982.6 2426.39  4988.6 2425.24  4998.6 2425.39
  5008.6 2424.45  5016.6 2422.80  5016.9 2422.30  5020.4 2422.30  5020.6 2422.80
  5028.6 2427.23  5048.7 2430.35  5058.7 2431.32  5088.7 2433.53  5102.4 2434.09
  5128.7 2436.17  5138.8 2436.68  5148.8 2437.69  5177.9 2440.05  5182.0 2440.05
#Mann=3,-1,0
  4826.5    0.07       0  5016.6    0.07       0  5020.6    0.07       0
Bank Sta=5016.6,5020.6
Exp/Cntr=0.3,0.1

Type RM Length L Ch R = 1,376,31,31,31
BEGIN DESCRIPTION:
748
END DESCRIPTION:
XS GIS Cut Line= 4
      1464120.47      6793269.44      1463990.71      6793207.99
      1463896.01      6793186.46      1463798.61      6793169.87
#Sta/Elev= 30
  4851.3 2433.50  4879.5 2431.92  4901.6 2429.85  4930.9 2427.61  4931.1 2427.11
  4934.6 2427.11  4934.9 2427.61  4938.4 2427.84  4945.9 2430.34  4955.6 2430.52
  4961.1 2430.03  4968.0 2430.91  4978.4 2431.01  4983.9 2430.22  4991.7 2430.86
  5000.7 2430.72  5021.9 2431.39  5041.8 2431.36  5059.8 2435.16  5064.9 2432.81
  5072.5 2433.00  5082.8 2431.97  5095.0 2431.98  5110.4 2434.20  5115.5 2434.25
  5141.1 2435.90  5164.0 2437.11  5170.6 2437.73  5184.3 2438.08  5190.8 2438.78
#Mann=5,-1,0
  4851.3    0.07       0  4930.9    0.07       0  4934.9    0.07       0
  4991.7    0.16       0  5141.1    0.07       0
Bank Sta=4930.9,4934.9
Exp/Cntr=0.3,0.1

Type RM Length L Ch R = 1,345,309,309,309
BEGIN DESCRIPTION:
747
END DESCRIPTION:
XS GIS Cut Line= 4
      1464135.68      6793234.72      1464016.21      6793187.37
      1463908.41      6793156.32      1463819.43      6793141.50
#Sta/Elev= 30
  4862.7 2433.04  4874.2 2432.70  4892.4 2431.52  4906.5 2430.13  4922.1 2429.58
  4928.0 2428.54  4946.4 2427.15  4977.2 2425.82  4981.8 2425.83  4989.2 2427.75
  4994.4 2427.75  5002.3 2429.19  5007.5 2427.04  5011.3 2424.96  5011.5 2424.46
  5015.0 2424.46  5015.3 2424.96  5023.7 2426.74  5041.2 2429.47  5046.4 2428.74
  5080.1 2429.45  5096.5 2430.31  5102.6 2431.14  5107.7 2431.14  5122.8 2433.73
  5127.9 2433.64  5152.0 2434.87  5177.8 2436.43  5188.8 2436.63  5193.6 2437.39
#Mann=5,-1,0
  4862.7    0.07       0  4977.2    0.16       0  5011.3    0.07       0
  5015.3    0.16       0  5152.0    0.07       0
Bank Sta=5011.3,5015.3
Exp/Cntr=0.3,0.1

Type RM Length L Ch R = 1,36,0,0,0
BEGIN DESCRIPTION:
746
END DESCRIPTION:
XS GIS Cut Line= 4
      1464259.39      6793039.42      1464030.00      6792913.00
      1463980.00      6792913.00      1463831.83      6793106.71
#Sta/Elev= 30
  4737.1 2430.71  4852.3 2426.29  4890.1 2423.52  4895.8 2422.23  4902.0 2421.86
  4937.1 2422.26  4977.2 2422.60  4983.0 2421.87  4999.0 2422.57  5004.0 2422.13
  5032.0 2421.56  5032.3 2421.06  5035.8 2421.06  5036.0 2421.56  5044.0 2423.08
  5049.0 2422.27  5055.3 2424.15  5063.5 2422.01  5069.8 2424.05  5078.1 2423.22
  5084.4 2424.81  5092.6 2424.16  5098.9 2426.74  5113.4 2426.06  5117.6 2427.83
  5119.7 2428.71  5142.5 2429.35  5148.8 2430.24  5198.6 2432.75  5292.9 2435.71
#Mann=5,-1,0
  4737.1    0.07       0  4937.1    0.16       0  5032.0    0.07       0
  5036.0    0.16       0  5117.6    0.07       0
Bank Sta=5032,5036
Exp/Cntr=0.3,0.1

Chan Stop Cuts=-1