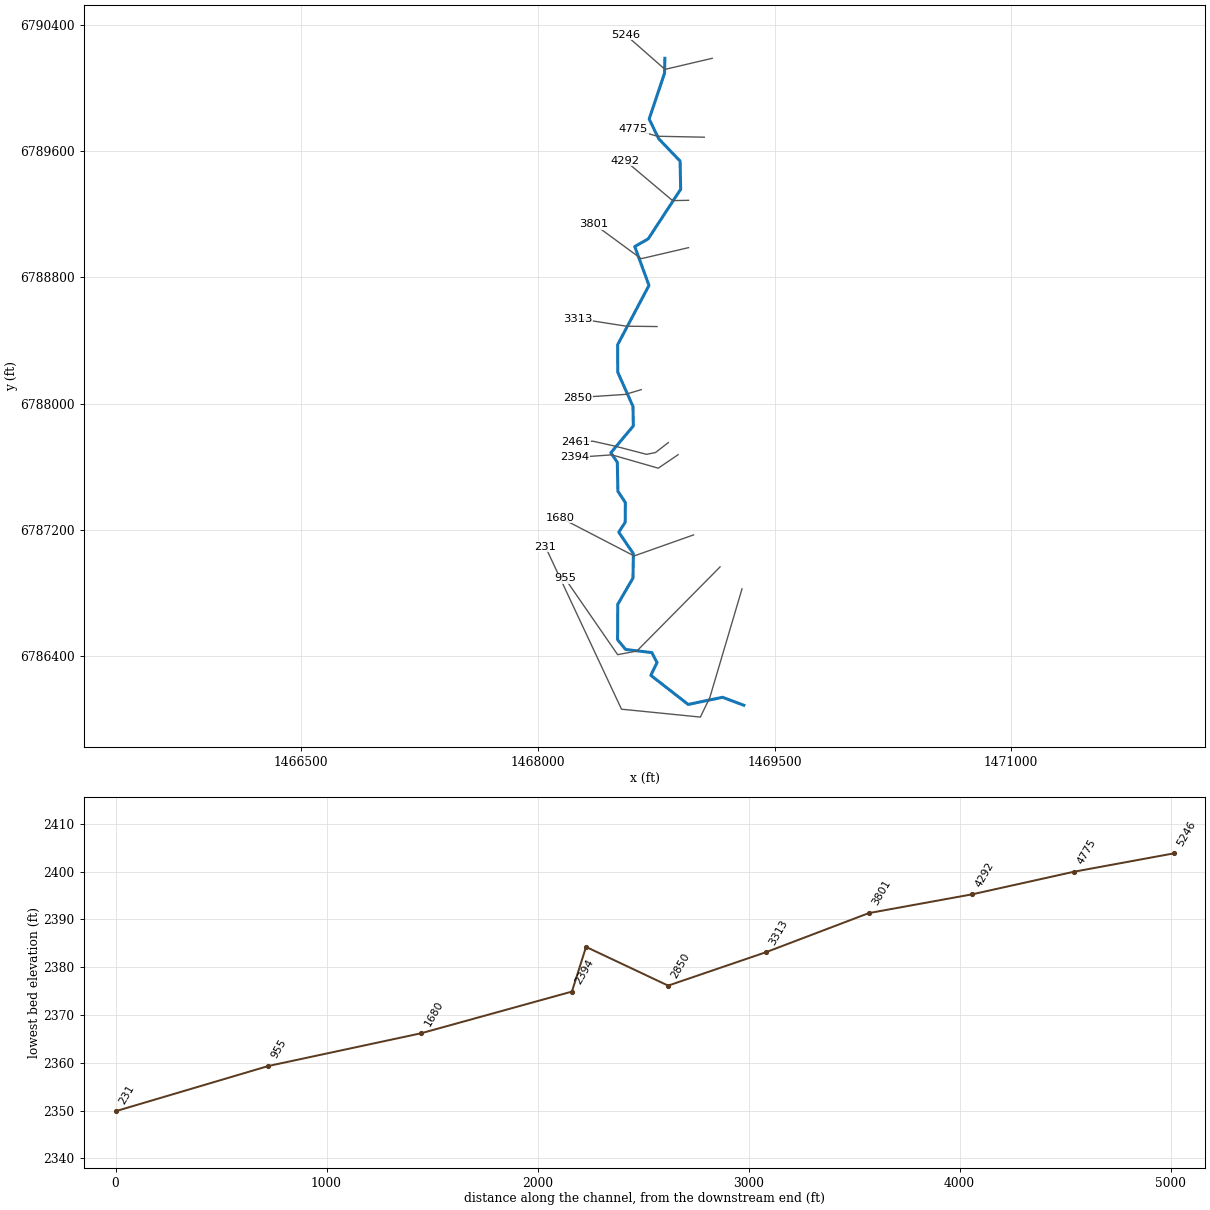
--- Elm 08.prj (project) ---

Proj Title=Elm 08 Base Level Engineering
Current Plan=p01
Default Exp/Contr=0.3,0.1
English Units
Geom File=g01
Flow File=f01
Plan File=p01
BEGIN DESCRIPTION:
Elm 08
END DESCRIPTION:

--- Elm 08.p01 (plan) ---

Plan Title=Multiple Run
Short Identifier=Multiple
Geom File=g01
Flow File=f01
Subcritical Flow
K Sum by GR= 0
Std Step Tol= 0.01
Critical Tol= 0.01
Num of Std Step Trials= 20
Max Error Tol= 0.3
Flow Tol Ratio= 0.001
Split Flow NTrial= 30
Split Flow Tol= 0.02
Split Flow Ratio= 0.02
Log Output Level= 0
Friction Slope Method= 1
Unsteady Friction Slope Method= 2
Unsteady Bridges Friction Slope Method= 1
Parabolic Critical Depth
Global Vel Dist=  1 , 1 , 1
Global Log Level= 0
CheckData=True
Encroach Param= -1, 0, 0, 0
BEGIN DESCRIPTION:
Multiple Run
END DESCRIPTION:

--- Elm 08.f01 (steady flow) ---

Flow Title=Multiple
Number of Profiles=7
Profile Names=10-year,25-year,50-year,1pct_min,100-year,1pct_plu,500-year
River Rch & RM= Elm 08,Reach-1,5246
     225     312     384     293     469     646     710
Boundary for River Rch & Prof#=Elm 08,Reach-1,1
Up Type=0
Dn Type=3
Dn Slope=0.005
Boundary for River Rch & Prof#=Elm 08,Reach-1,2
Up Type=0
Dn Type=3
Dn Slope=0.005
Boundary for River Rch & Prof#=Elm 08,Reach-1,3
Up Type=0
Dn Type=3
Dn Slope=0.005
Boundary for River Rch & Prof#=Elm 08,Reach-1,4
Up Type=0
Dn Type=3
Dn Slope=0.005
Boundary for River Rch & Prof#=Elm 08,Reach-1,5
Up Type=0
Dn Type=3
Dn Slope=0.005
Boundary for River Rch & Prof#=Elm 08,Reach-1,6
Up Type=0
Dn Type=3
Dn Slope=0.005
Boundary for River Rch & Prof#=Elm 08,Reach-1,7
Up Type=0
Dn Type=3
Dn Slope=0.005

--- Elm 08.g01 (geometry) ---

Geom Title=Existing Conditions

River Reach=Elm 08,Reach-1
Reach XY= 30
      1468805.00      6790188.00      1468802.90      6790093.87
      1468705.37      6789803.27      1468765.76      6789678.32
      1468901.46      6789536.54      1468905.04      6789357.98
      1468699.32      6789043.62      1468614.05      6788995.00
      1468704.25      6788748.68      1468505.51      6788372.79
      1468506.22      6788198.50      1468602.75      6787982.06
      1468605.06      6787857.99      1468462.32      6787688.10
      1468503.61      6787627.57      1468507.26      6787443.94
      1468554.49      6787372.78      1468553.62      6787248.44
      1468512.81      6787184.59      1468605.50      6787048.21
      1468602.76      6786893.93      1468506.20      6786727.50
      1468505.32      6786503.02      1468556.22      6786441.44
      1468722.31      6786421.72      1468755.27      6786358.23
      1468715.98      6786277.63      1468952.70      6786093.09
      1469170.17      6786138.48      1469305.00      6786088.00

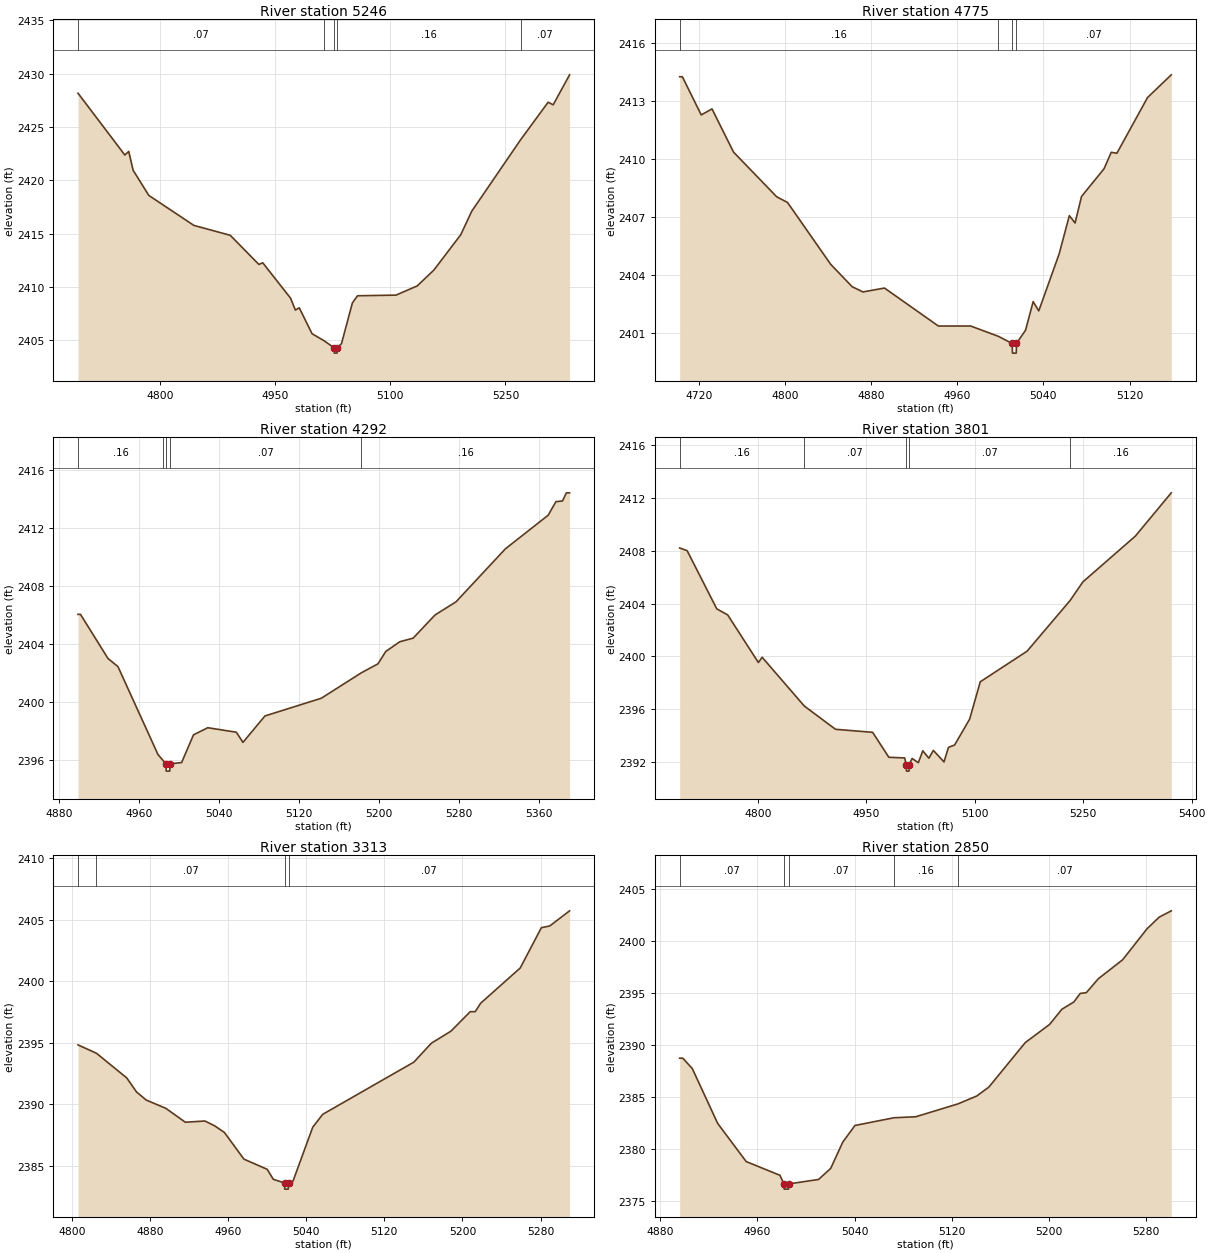
Type RM Length L Ch R = 1,5246,471,471,471
BEGIN DESCRIPTION:
414
END DESCRIPTION:
XS GIS Cut Line= 3
      1469105.00      6790188.00      1468805.64      6790117.74
      1468554.98      6790338.02
#Sta/Elev= 30
  4692.5 2428.17  4753.6 2422.37  4758.7 2422.71  4764.4 2420.94  4784.9 2418.58
  4843.6 2415.77  4891.1 2414.84  4928.4 2412.11  4933.5 2412.26  4969.8 2408.94
  4976.0 2407.83  4981.1 2408.04  4997.8 2405.61  5013.3 2404.96  5026.6 2404.29
  5026.9 2403.79  5030.4 2403.79  5030.6 2404.29  5036.2 2404.68  5050.4 2408.50
  5057.1 2409.17  5107.3 2409.23  5134.9 2410.09  5156.7 2411.58  5191.8 2414.90
  5206.0 2417.09  5269.7 2423.79  5305.7 2427.32  5312.3 2427.08  5333.7 2429.89
#Mann=5,-1,0
  4692.5    0.07       0  5013.3    0.16       0  5026.6    0.07       0
  5030.6    0.16       0  5269.7    0.07       0
Bank Sta=5026.6,5030.6
Exp/Cntr=0.3,0.1

Type RM Length L Ch R = 1,4775,483,483,483
BEGIN DESCRIPTION:
413
END DESCRIPTION:
XS GIS Cut Line= 3
      1469055.03      6789688.00      1468757.50      6789694.03
      1468605.01      6789738.00
#Sta/Elev= 30
  4702.4 2414.24  4704.9 2414.24  4722.4 2412.27  4732.4 2412.58  4752.4 2410.35
  4792.5 2408.04  4802.5 2407.75  4842.5 2404.56  4862.5 2403.40  4872.5 2403.13
  4892.5 2403.33  4942.5 2401.37  4972.5 2401.37  4998.1 2400.84  5011.0 2400.47
  5011.3 2399.97  5014.8 2399.97  5015.0 2400.47  5023.4 2401.15  5030.5 2402.63
  5035.7 2402.15  5054.6 2405.09  5064.1 2407.07  5069.4 2406.69  5075.4 2408.06
  5096.3 2409.49  5103.0 2410.34  5108.2 2410.29  5136.7 2413.17  5158.7 2414.34
#Mann=4,-1,0
  4702.4    0.16       0  4998.1    0.07       0  5011.0    0.07       0
  5015.0    0.07       0
Bank Sta=5011,5015
Exp/Cntr=0.3,0.1

Type RM Length L Ch R = 1,4292,491,491,491
BEGIN DESCRIPTION:
412
END DESCRIPTION:
XS GIS Cut Line= 3
      1468955.02      6789288.00      1468853.84      6789286.12
      1468555.02      6789537.98
#Sta/Elev= 30
  4898.8 2406.04  4901.3 2406.04  4928.8 2403.00  4938.8 2402.44  4978.8 2396.39
  4984.1 2395.96  4986.8 2395.74  4987.1 2395.24  4990.6 2395.24  4990.8 2395.74
  5002.5 2395.83  5014.4 2397.74  5028.7 2398.23  5057.3 2397.92  5063.9 2397.22
  5085.9 2399.04  5142.3 2400.26  5182.3 2402.01  5199.0 2402.63  5206.8 2403.48
  5220.8 2404.15  5234.2 2404.40  5256.2 2406.00  5277.1 2406.90  5326.5 2410.55
  5369.4 2412.87  5377.1 2413.80  5383.7 2413.85  5387.6 2414.41  5390.8 2414.41
#Mann=5,-1,0
  4898.8    0.16       0  4984.1    0.07       0  4986.8    0.07       0
  4990.8    0.07       0  5182.3    0.16       0
Bank Sta=4986.8,4990.8
Exp/Cntr=0.3,0.1

Type RM Length L Ch R = 1,3801,488,488,488
BEGIN DESCRIPTION:
411
END DESCRIPTION:
XS GIS Cut Line= 3
      1468954.98      6788988.00      1468654.64      6788917.95
      1468354.97      6789138.02
#Sta/Elev= 30
  4691.6 2408.21  4701.9 2408.01  4742.9 2403.60  4758.0 2403.14  4800.5 2399.53
  4805.7 2399.93  4863.9 2396.24  4907.2 2394.47  4958.6 2394.24  4981.0 2392.35
  5002.9 2392.30  5005.1 2391.80  5005.4 2391.30  5008.9 2391.30  5009.1 2391.80
  5013.3 2392.26  5021.8 2391.94  5028.0 2392.84  5036.4 2392.28  5042.6 2392.87
  5057.3 2392.00  5063.5 2393.10  5072.0 2393.28  5092.8 2395.24  5107.5 2398.07
  5172.3 2400.39  5231.8 2404.23  5249.5 2405.64  5322.1 2409.11  5371.8 2412.39
#Mann=5,-1,0
  4691.6    0.16       0  4863.9    0.07       0  5005.1    0.07       0
  5009.1    0.07       0  5231.8    0.16       0
Bank Sta=5005.1,5009.1
Exp/Cntr=0.3,0.1

Type RM Length L Ch R = 1,3313,463,463,463
BEGIN DESCRIPTION:
410
END DESCRIPTION:
XS GIS Cut Line= 3
      1468754.97      6788488.00      1468561.08      6788490.20
      1468254.99      6788538.00
#Sta/Elev= 30
  4806.1 2394.84  4825.0 2394.16  4856.1 2392.15  4866.1 2391.01  4876.1 2390.35
  4896.1 2389.68  4916.1 2388.55  4936.1 2388.65  4946.1 2388.26  4956.1 2387.72
  4976.1 2385.55  5000.0 2384.72  5006.2 2383.91  5017.8 2383.61  5018.0 2383.11
  5021.5 2383.11  5021.8 2383.61  5026.4 2383.76  5046.6 2388.14  5056.8 2389.19
  5150.3 2393.44  5168.1 2394.97  5188.3 2395.96  5208.0 2397.54  5213.1 2397.54
  5218.7 2398.23  5259.2 2401.09  5280.9 2404.37  5289.5 2404.51  5309.8 2405.74
#Mann=4,-1,0
  4806.1    0.16       0  4825.0    0.07       0  5017.8    0.07       0
  5021.8    0.07       0
Bank Sta=5017.8,5021.8
Exp/Cntr=0.3,0.1

Type RM Length L Ch R = 1,2850,389,389,389
BEGIN DESCRIPTION:
409
END DESCRIPTION:
XS GIS Cut Line= 3
      1468654.96      6788087.99      1468555.24      6788058.10
      1468255.01      6788038.00
#Sta/Elev= 30
  4895.9 2388.72  4898.5 2388.72  4906.3 2387.72  4927.2 2382.45  4950.7 2378.78
  4978.5 2377.46  4981.8 2376.63  4982.0 2376.13  4985.5 2376.13  4985.8 2376.63
  5010.3 2377.06  5020.3 2378.12  5030.3 2380.66  5040.3 2382.25  5072.3 2382.99
  5090.4 2383.09  5125.0 2384.32  5140.6 2385.08  5150.6 2385.94  5180.6 2390.22
  5200.7 2391.97  5210.7 2393.42  5220.7 2394.13  5225.9 2394.95  5230.9 2395.02
  5240.8 2396.36  5260.8 2398.18  5280.9 2401.16  5290.9 2402.28  5300.9 2402.89
#Mann=5,-1,0
  4895.9    0.07       0  4981.8    0.07       0  4985.8    0.07       0
  5072.3    0.16       0  5125.0    0.07       0
Bank Sta=4981.8,4985.8
Exp/Cntr=0.3,0.1

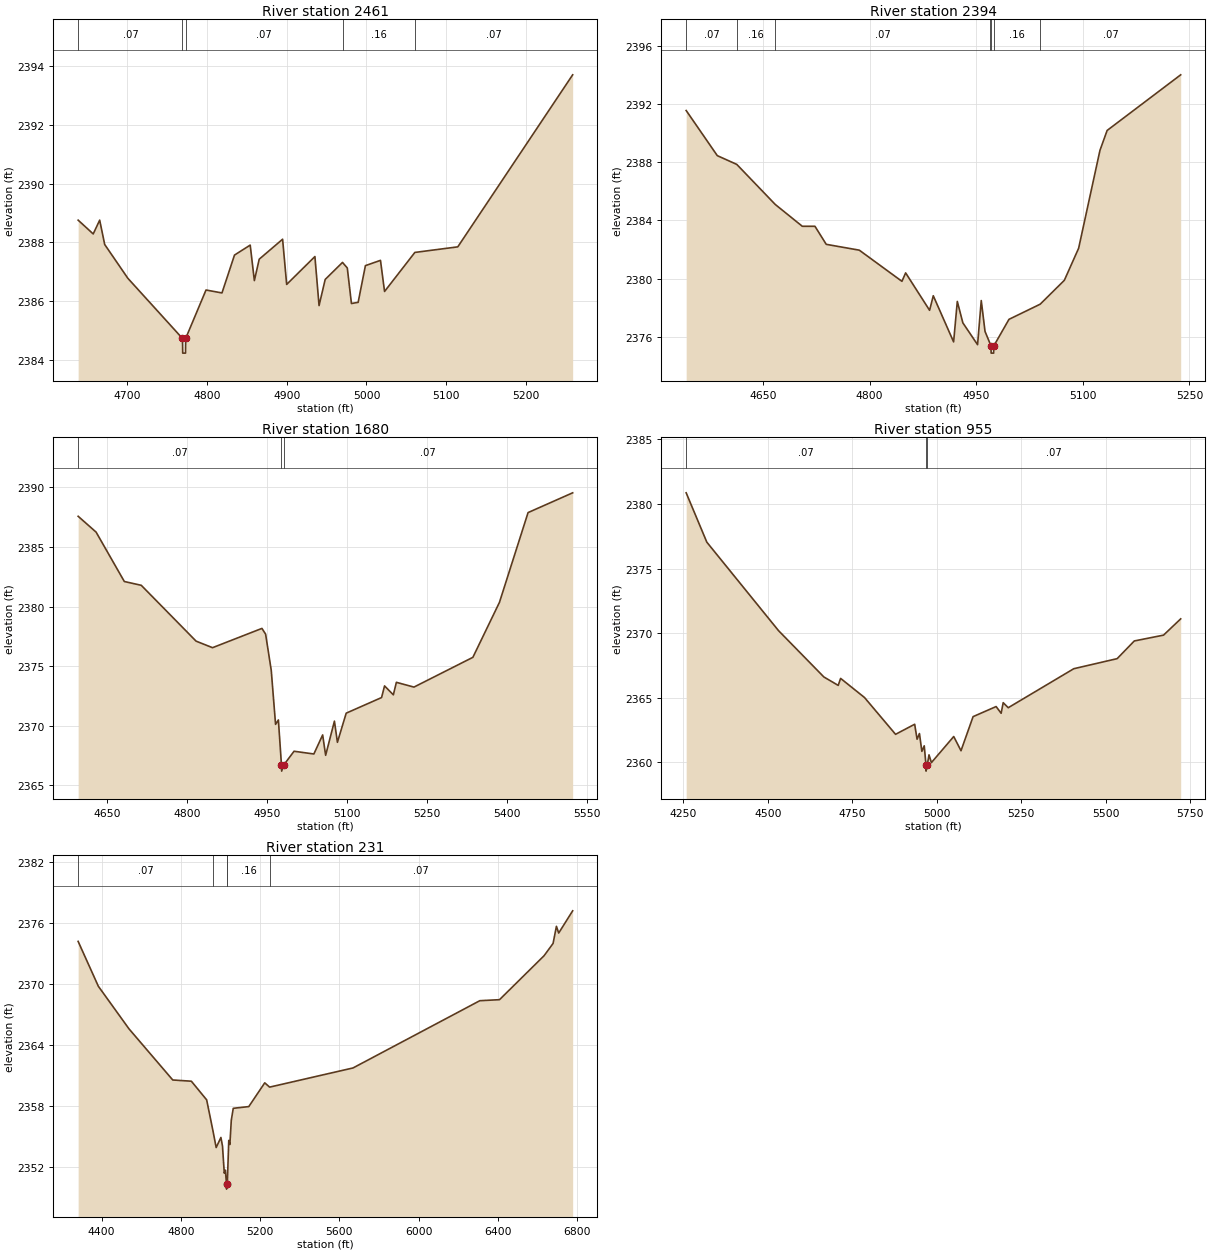
Type RM Length L Ch R = 1,2461,67,67,67
BEGIN DESCRIPTION:
751
END DESCRIPTION:
XS GIS Cut Line= 6
      1468827.09      6787752.86      1468745.51      6787689.58
      1468689.10      6787678.14      1468492.42      6787729.22
      1468349.87      6787761.24      1468240.15      6787757.43
#Sta/Elev= 30
  4638.6 2388.76  4657.5 2388.29  4665.6 2388.76  4671.9 2387.93  4700.9 2386.78
  4769.4 2384.73  4769.7 2384.23  4773.2 2384.23  4773.4 2384.73  4798.9 2386.38
  4818.9 2386.28  4834.6 2387.57  4854.3 2387.91  4859.5 2386.70  4865.6 2387.43
  4894.9 2388.11  4900.0 2386.57  4935.4 2387.52  4940.6 2385.85  4948.3 2386.74
  4970.0 2387.32  4976.0 2387.13  4981.2 2385.92  4989.6 2385.96  4998.7 2387.21
  5017.6 2387.39  5022.7 2386.33  5060.7 2387.66  5114.5 2387.85  5258.5 2393.71
#Mann=5,-1,0
  4638.6    0.07       0  4769.4    0.07       0  4773.4    0.07       0
  4970.0    0.16       0  5060.7    0.07       0
Bank Sta=4769.4,4773.4
Exp/Cntr=0.3,0.1

Type RM Length L Ch R = 1,2394,714,714,714
BEGIN DESCRIPTION:
408
END DESCRIPTION:
XS GIS Cut Line= 4
      1468888.83      6787675.86      1468763.05      6787590.48
      1468468.83      6787674.84      1468231.71      6787658.32
#Sta/Elev= 30
  4541.9 2391.54  4585.7 2388.44  4613.1 2387.84  4667.2 2385.09  4705.3 2383.59
  4723.1 2383.59  4739.0 2382.35  4785.5 2381.95  4845.5 2379.81  4850.7 2380.39
  4884.4 2377.82  4889.6 2378.82  4918.2 2375.65  4923.4 2378.43  4931.2 2376.96
  4951.9 2375.46  4957.1 2378.49  4962.4 2376.37  4969.6 2375.52  4970.8 2375.38
  4971.0 2374.88  4974.5 2374.88  4974.8 2375.38  4996.1 2377.20  5040.0 2378.24
  5074.0 2379.88  5094.1 2382.08  5124.1 2388.80  5134.2 2390.17  5237.7 2393.99
#Mann=7,-1,0
  4541.9    0.07       0  4613.1    0.16       0  4667.2    0.07       0
  4969.6    0.16       0  4970.8    0.07       0  4974.8    0.16       0
  5040.0    0.07       0
Bank Sta=4970.8,4974.8
Exp/Cntr=0.3,0.1

Type RM Length L Ch R = 1,1680,725,725,725
BEGIN DESCRIPTION:
750
END DESCRIPTION:
XS GIS Cut Line= 3
      1468986.73      6787167.55      1468610.05      6787034.26
      1468140.66      6787277.64
#Sta/Elev= 30
  4595.3 2387.58  4629.0 2386.25  4682.0 2382.10  4713.8 2381.78  4816.7 2377.09
  4847.6 2376.54  4940.3 2378.16  4947.2 2377.68  4957.8 2374.64  4965.9 2370.10
  4971.2 2370.47  4977.0 2366.67  4977.3 2366.17  4981.0 2366.67  5000.6 2367.84
  5037.8 2367.61  5054.3 2369.21  5059.9 2367.50  5076.4 2370.37  5082.0 2368.59
  5098.5 2371.04  5164.9 2372.35  5170.5 2373.33  5187.0 2372.58  5192.7 2373.63
  5225.7 2373.23  5336.3 2375.73  5386.2 2380.35  5439.9 2387.89  5523.6 2389.55
#Mann=3,-1,0
  4595.3    0.07       0  4977.0    0.07       0  4981.0    0.07       0
Bank Sta=4977,4981
Exp/Cntr=0.3,0.1

Type RM Length L Ch R = 1,955,724,724,724
BEGIN DESCRIPTION:
749
END DESCRIPTION:
XS GIS Cut Line= 4
      1469154.72      6786964.71      1468627.43      6786431.62
      1468505.74      6786408.45      1468170.56      6786893.89
#Sta/Elev= 30
  4258.7 2380.86  4319.8 2377.04  4532.0 2370.19  4666.3 2366.60  4708.7 2365.95
  4715.8 2366.49  4786.5 2365.01  4878.4 2362.16  4935.0 2362.94  4942.1 2361.78
  4949.1 2362.22  4956.3 2360.84  4963.3 2361.27  4968.4 2359.81  4968.6 2359.31
  4972.4 2359.81  4977.4 2360.57  4984.5 2359.97  5050.6 2361.99  5072.1 2360.89
  5107.9 2363.53  5176.0 2364.31  5190.9 2363.79  5197.0 2364.61  5211.9 2364.22
  5405.9 2367.24  5534.3 2368.02  5585.0 2369.39  5671.5 2369.84  5722.3 2371.10
#Mann=3,-1,0
  4258.7    0.07       0  4968.4    0.07       0  4972.4    0.07       0
Bank Sta=4968.4,4972.4
Exp/Cntr=0.3,0.1

Type RM Length L Ch R = 1,231,0,0,0
BEGIN DESCRIPTION:
407
END DESCRIPTION:
XS GIS Cut Line= 5
      1469293.82      6786825.70      1469090.00      6786137.44
      1469030.00      6786013.00      1468530.00      6786063.00
      1468047.99      6787092.17
#Sta/Elev= 30
  4281.9 2374.16  4383.8 2369.76  4538.4 2365.58  4759.2 2360.56  4853.1 2360.44
  4930.3 2358.61  4962.1 2355.57  4978.3 2353.93  5002.2 2354.92  5010.2 2354.07
  5019.2 2351.42  5024.8 2351.71  5030.4 2350.35  5030.6 2349.85  5034.4 2350.35
  5041.8 2354.63  5047.4 2354.23  5054.6 2356.61  5064.5 2357.78  5142.9 2357.95
  5223.3 2360.28  5248.0 2359.86  5668.7 2361.74  6308.4 2368.34  6407.8 2368.44
  6632.4 2372.75  6678.0 2373.96  6694.9 2375.64  6706.4 2374.98  6776.8 2377.16
#Mann=5,-1,0
  4281.9    0.07       0  4962.1    0.16       0  5030.4    0.07       0
  5034.4    0.16       0  5248.0    0.07       0
Bank Sta=5030.4,5034.4
Exp/Cntr=0.3,0.1

Chan Stop Cuts=-1