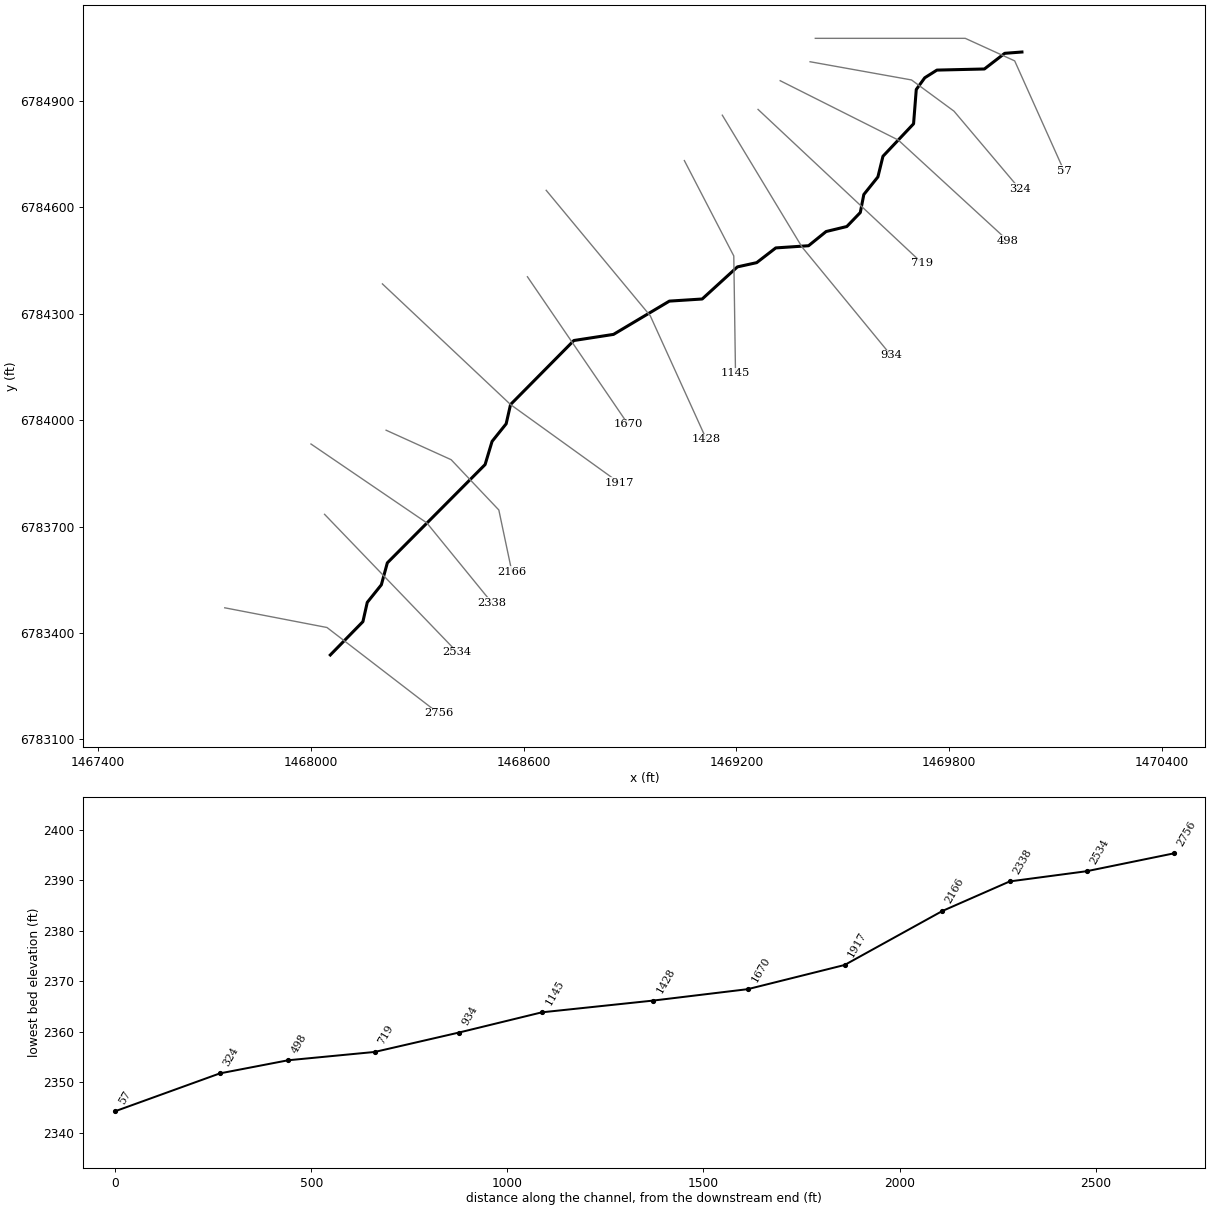
--- Elm 09.prj (project) ---

Proj Title=Elm 09 Base Level Engineering
Current Plan=p01
Default Exp/Contr=0.3,0.1
English Units
Geom File=g01
Flow File=f01
Plan File=p01
BEGIN DESCRIPTION:
Elm 09
END DESCRIPTION:

--- Elm 09.p01 (plan) ---

Plan Title=Multiple Run
Short Identifier=Multiple
Geom File=g01
Flow File=f01
Subcritical Flow
K Sum by GR= 0
Std Step Tol= 0.01
Critical Tol= 0.01
Num of Std Step Trials= 20
Max Error Tol= 0.3
Flow Tol Ratio= 0.001
Split Flow NTrial= 30
Split Flow Tol= 0.02
Split Flow Ratio= 0.02
Log Output Level= 0
Friction Slope Method= 1
Unsteady Friction Slope Method= 2
Unsteady Bridges Friction Slope Method= 1
Parabolic Critical Depth
Global Vel Dist=  1 , 1 , 1
Global Log Level= 0
CheckData=True
Encroach Param= -1, 0, 0, 0
BEGIN DESCRIPTION:
Multiple Run
END DESCRIPTION:

--- Elm 09.f01 (steady flow) ---

Flow Title=Multiple
Number of Profiles=7
Profile Names=10-year,25-year,50-year,1pct_min,100-year,1pct_plu,500-year
River Rch & RM= Elm 09,Reach-1,2756
     190     263     324     248     397     547     603
Boundary for River Rch & Prof#=Elm 09,Reach-1,1
Up Type=0
Dn Type=3
Dn Slope=0.005
Boundary for River Rch & Prof#=Elm 09,Reach-1,2
Up Type=0
Dn Type=3
Dn Slope=0.005
Boundary for River Rch & Prof#=Elm 09,Reach-1,3
Up Type=0
Dn Type=3
Dn Slope=0.005
Boundary for River Rch & Prof#=Elm 09,Reach-1,4
Up Type=0
Dn Type=3
Dn Slope=0.005
Boundary for River Rch & Prof#=Elm 09,Reach-1,5
Up Type=0
Dn Type=3
Dn Slope=0.005
Boundary for River Rch & Prof#=Elm 09,Reach-1,6
Up Type=0
Dn Type=3
Dn Slope=0.005
Boundary for River Rch & Prof#=Elm 09,Reach-1,7
Up Type=0
Dn Type=3
Dn Slope=0.005

--- Elm 09.g01 (geometry) ---

Geom Title=Existing Conditions

River Reach=Elm 09,Reach-1
Reach XY= 30
      1468055.00      6783338.00      1468146.91      6783431.92
      1468159.18      6783486.27      1468198.90      6783535.81
      1468215.76      6783597.68      1468491.38      6783874.79
      1468511.10      6783940.19      1468550.81      6783989.74
      1468563.14      6784044.06      1468741.70      6784224.60
      1468853.41      6784241.83      1469010.97      6784335.67
      1469103.50      6784341.62      1469202.71      6784432.15
      1469257.17      6784444.14      1469310.97      6784485.67
      1469403.42      6784491.82      1469452.85      6784531.85
      1469511.34      6784546.02      1469549.27      6784585.45
      1469559.20      6784636.24      1469598.90      6784685.81
      1469613.16      6784744.05      1469699.46      6784835.58
      1469707.07      6784932.31      1469730.98      6784965.34
      1469765.27      6784987.01      1469899.11      6784990.14
      1469956.51      6785034.35      1470005.00      6785038.00

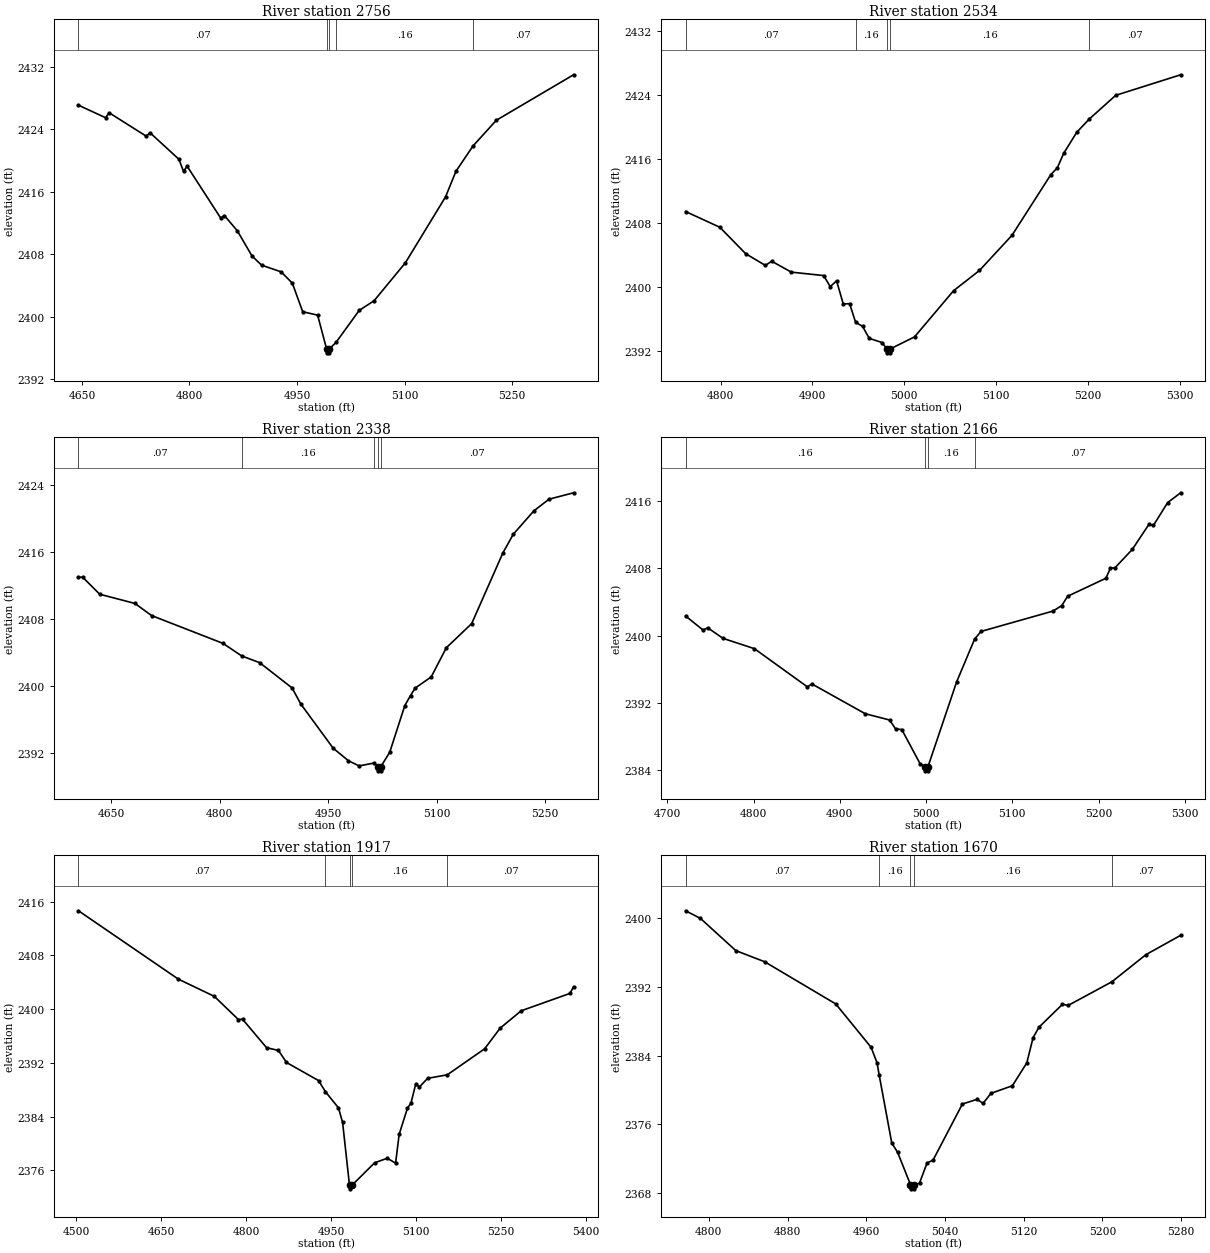
Type RM Length L Ch R = 1,2756,222,222,222
BEGIN DESCRIPTION:
elmc252
END DESCRIPTION:
XS GIS Cut Line= 3
      1467757.42      6783470.99      1468045.63      6783415.43
      1468360.37      6783173.32
#Sta/Elev= 30
  4645.2 2427.10  4682.9 2425.50  4688.0 2426.13  4739.9 2423.12  4744.9 2423.58
  4785.3 2420.17  4791.7 2418.62  4796.8 2419.28  4843.6 2412.63  4848.7 2412.96
  4866.8 2411.00  4887.2 2407.78  4900.6 2406.60  4927.9 2405.74  4943.5 2404.29
  4958.0 2400.63  4978.8 2400.19  4991.3 2395.86  4991.5 2395.36  4995.0 2395.36
  4995.3 2395.86  5004.9 2396.75  5036.8 2400.80  5057.6 2402.04  5101.2 2406.90
  5157.3 2415.36  5171.8 2418.64  5195.7 2421.89  5228.1 2425.17  5335.8 2431.00
#Mann=5,-1,0
  4645.2    0.07       0  4991.3    0.07       0  4995.3    0.07       0
  5004.9    0.16       0  5195.7    0.07       0
Bank Sta=4991.3,4995.3
Exp/Cntr=0.3,0.1

Type RM Length L Ch R = 1,2534,196,196,196
BEGIN DESCRIPTION:
elmc251
END DESCRIPTION:
XS GIS Cut Line= 2
      1468038.78      6783734.55      1468412.79      6783345.87
#Sta/Elev= 30
  4761.8 2409.48  4799.0 2407.52  4827.3 2404.21  4848.7 2402.75  4855.6 2403.27
  4877.0 2401.91  4912.2 2401.48  4919.4 2400.10  4926.3 2400.82  4933.6 2397.93
  4940.5 2397.97  4947.0 2395.65  4954.6 2395.14  4961.9 2393.64  4976.0 2393.11
  4980.9 2392.33  4981.2 2391.83  4984.7 2391.83  4984.9 2392.33  5011.2 2393.82
  5053.7 2399.58  5082.0 2402.12  5117.5 2406.52  5159.7 2414.08  5166.9 2414.96
  5173.8 2416.76  5188.0 2419.38  5201.7 2421.04  5230.4 2423.99  5301.2 2426.56
#Mann=5,-1,0
  4761.8    0.07       0  4947.0    0.16       0  4980.9    0.07       0
  4984.9    0.16       0  5201.7    0.07       0
Bank Sta=4980.9,4984.9
Exp/Cntr=0.3,0.1

Type RM Length L Ch R = 1,2338,172,172,172
BEGIN DESCRIPTION:
elmc209
END DESCRIPTION:
XS GIS Cut Line= 3
      1468000.48      6783932.80      1468326.88      6783710.57
      1468510.47      6783485.40
#Sta/Elev= 30
  4604.3 2412.98  4610.1 2412.98  4633.7 2410.94  4682.4 2409.84  4705.5 2408.39
  4804.4 2405.06  4830.2 2403.56  4855.2 2402.75  4900.0 2399.73  4912.2 2397.79
  4956.9 2392.52  4977.9 2391.03  4992.8 2390.40  5013.3 2390.74  5018.9 2390.31
  5019.1 2389.81  5022.6 2389.81  5022.9 2390.31  5035.2 2392.03  5056.1 2397.62
  5064.0 2398.82  5070.4 2399.71  5092.7 2401.05  5113.5 2404.53  5148.7 2407.43
  5191.8 2415.87  5206.2 2418.11  5234.7 2420.91  5255.7 2422.31  5289.7 2423.08
#Mann=5,-1,0
  4604.3    0.07       0  4830.2    0.16       0  5013.3    0.07       0
  5018.9    0.07       0  5022.9    0.07       0
Bank Sta=5018.9,5022.9
Exp/Cntr=0.3,0.1

Type RM Length L Ch R = 1,2166,249,249,249
BEGIN DESCRIPTION:
elmc250
END DESCRIPTION:
XS GIS Cut Line= 4
      1468212.33      6783971.67      1468395.67      6783888.56
      1468530.11      6783746.78      1468566.78      6783573.19
#Sta/Elev= 30
  4721.1 2402.34  4741.3 2400.68  4746.8 2400.94  4764.4 2399.69  4800.9 2398.46
  4862.2 2393.93  4867.7 2394.26  4929.4 2390.73  4957.7 2389.98  4964.6 2388.92
  4971.8 2388.85  4992.9 2384.81  4998.2 2384.44  4998.4 2383.94  5001.9 2383.94
  5002.2 2384.44  5035.4 2394.51  5056.3 2399.61  5063.7 2400.51  5147.2 2402.93
  5157.4 2403.59  5164.1 2404.69  5208.5 2406.83  5213.8 2408.04  5218.9 2408.06
  5239.2 2410.27  5258.4 2413.24  5263.6 2413.11  5280.1 2415.82  5295.2 2416.99
#Mann=4,-1,0
  4721.1    0.16       0  4998.2    0.07       0  5002.2    0.16       0
  5056.3    0.07       0
Bank Sta=4998.2,5002.2
Exp/Cntr=0.3,0.1

Type RM Length L Ch R = 1,1917,247,247,247
BEGIN DESCRIPTION:
elmc208
END DESCRIPTION:
XS GIS Cut Line= 3
      1468201.86      6784384.19      1468563.14      6784044.06
      1468870.07      6783823.08
#Sta/Elev= 30
  4503.8 2414.62  4680.2 2404.45  4743.7 2401.89  4786.2 2398.44  4793.5 2398.49
  4836.0 2394.25  4857.0 2393.84  4871.2 2392.05  4927.8 2389.36  4940.0 2387.70
  4963.0 2385.30  4970.3 2383.13  4982.5 2373.75  4982.7 2373.25  4986.5 2373.75
  5026.9 2377.13  5049.3 2377.80  5063.9 2377.07  5070.2 2381.36  5084.9 2385.27
  5091.0 2385.98  5099.6 2388.89  5105.8 2388.39  5120.5 2389.69  5155.3 2390.22
  5221.1 2394.08  5248.7 2397.17  5285.7 2399.74  5372.0 2402.33  5378.2 2403.32
#Mann=5,-1,0
  4503.8    0.07       0  4940.0    0.16       0  4982.5    0.07       0
  4986.5    0.16       0  5155.3    0.07       0
Bank Sta=4982.5,4986.5
Exp/Cntr=0.3,0.1

Type RM Length L Ch R = 1,1670,242,242,242
BEGIN DESCRIPTION:
elmc249
END DESCRIPTION:
XS GIS Cut Line= 2
      1468610.77      6784404.34      1468894.34      6783988.77
#Sta/Elev= 30
  4776.4 2400.87  4791.5 2399.98  4827.4 2396.23  4856.7 2394.93  4929.0 2390.01
  4964.9 2384.96  4971.0 2383.13  4973.1 2381.73  4985.9 2373.81  4991.9 2372.70
  5004.9 2368.96  5005.1 2368.46  5008.6 2368.46  5008.9 2368.96  5014.1 2369.12
  5021.8 2371.49  5027.8 2371.79  5057.7 2378.35  5072.6 2378.89  5078.7 2378.42
  5086.7 2379.59  5108.5 2380.48  5123.1 2383.13  5129.5 2386.07  5135.5 2387.30
  5159.3 2389.96  5165.4 2389.85  5209.7 2392.60  5244.1 2395.75  5279.5 2398.01
#Mann=5,-1,0
  4776.4    0.07       0  4973.1    0.16       0  5004.9    0.07       0
  5008.9    0.16       0  5209.7    0.07       0
Bank Sta=5004.9,5008.9
Exp/Cntr=0.3,0.1

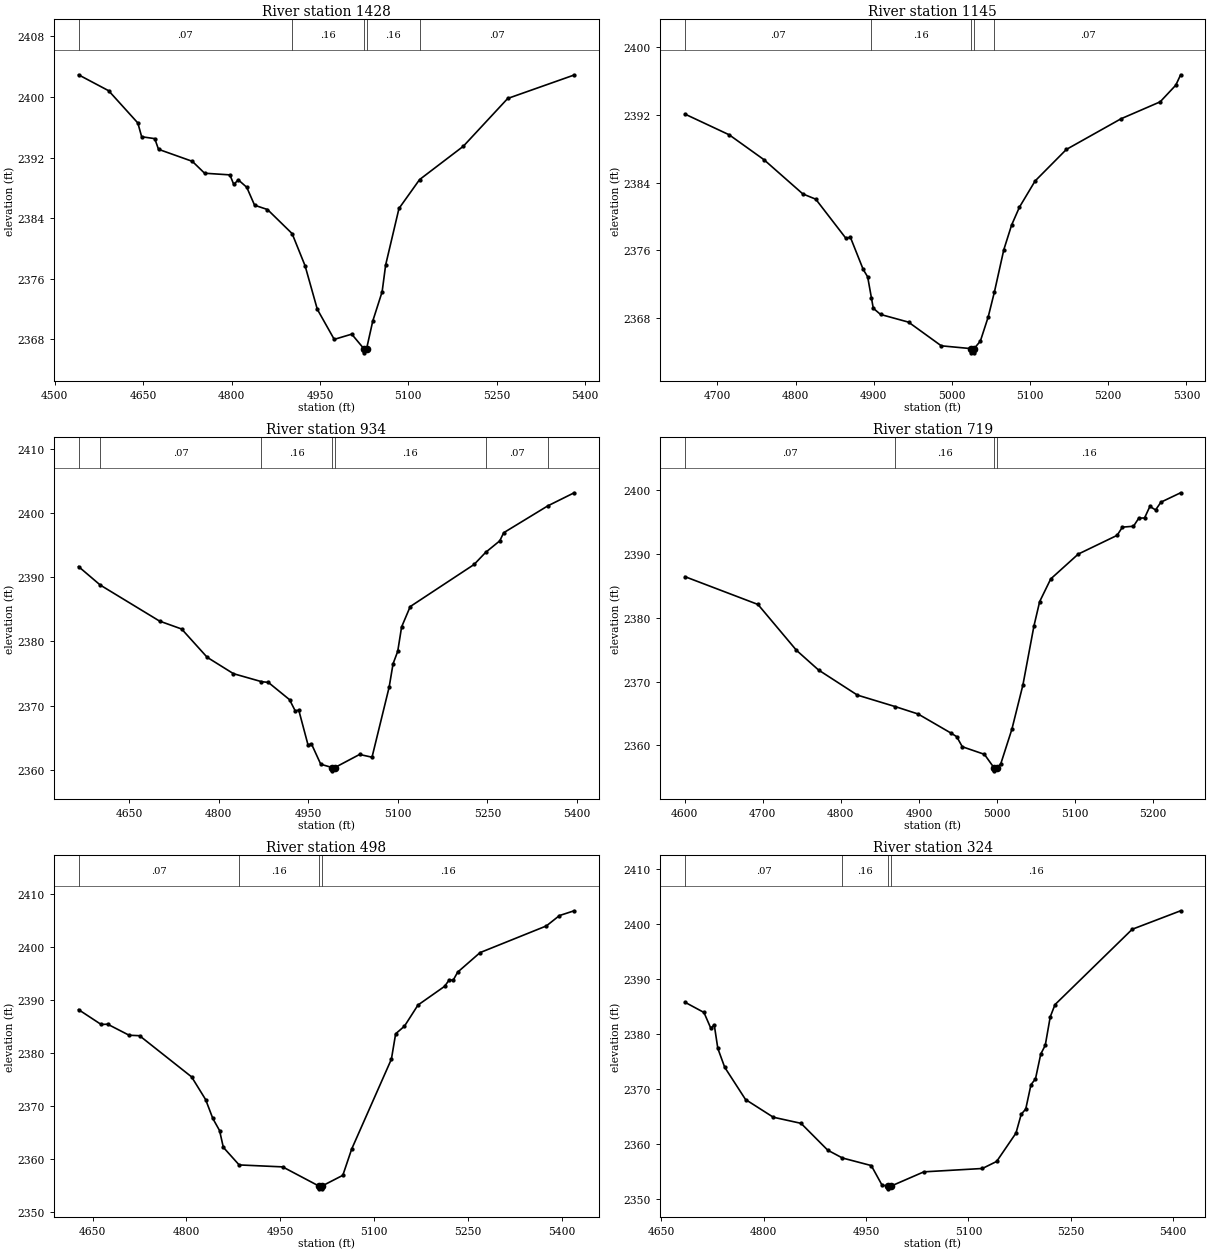
Type RM Length L Ch R = 1,1428,283,283,283
BEGIN DESCRIPTION:
elmc207
END DESCRIPTION:
XS GIS Cut Line= 3
      1468663.69      6784648.06      1468957.18      6784294.11
      1469115.06      6783946.70
#Sta/Elev= 30
  4540.2 2402.94  4591.4 2400.83  4640.9 2396.57  4647.4 2394.75  4669.6 2394.50
  4676.0 2393.09  4733.4 2391.50  4754.2 2389.93  4797.2 2389.71  4803.7 2388.45
  4811.5 2389.05  4825.8 2388.07  4839.1 2385.70  4861.0 2385.13  4902.8 2381.95
  4924.8 2377.70  4945.6 2371.94  4974.3 2367.97  5004.0 2368.66  5025.1 2366.69
  5025.3 2366.19  5029.1 2366.69  5039.7 2370.39  5055.6 2374.26  5061.6 2377.81
  5084.2 2385.27  5119.2 2389.09  5193.4 2393.49  5268.8 2399.81  5381.6 2402.91
#Mann=5,-1,0
  4540.2    0.07       0  4902.8    0.16       0  5025.1    0.07       0
  5029.1    0.16       0  5119.2    0.07       0
Bank Sta=5025.1,5029.1
Exp/Cntr=0.3,0.1

Type RM Length L Ch R = 1,1145,211,211,211
BEGIN DESCRIPTION:
elmc248
END DESCRIPTION:
XS GIS Cut Line= 3
      1469053.22      6784731.89      1469192.56      6784463.00
      1469197.43      6784131.79
#Sta/Elev= 30
  4658.5 2392.10  4715.1 2389.65  4759.4 2386.72  4809.3 2382.66  4825.8 2382.04
  4864.4 2377.41  4870.1 2377.54  4886.5 2373.73  4892.2 2372.86  4897.1 2370.33
  4899.4 2369.14  4908.7 2368.41  4944.5 2367.50  4986.4 2364.70  5024.4 2364.37
  5024.6 2363.87  5028.1 2363.87  5028.4 2364.37  5036.4 2365.26  5046.4 2368.11
  5054.4 2371.08  5066.4 2376.07  5076.4 2378.99  5086.4 2381.10  5106.4 2384.19
  5146.4 2387.92  5216.4 2391.55  5266.4 2393.55  5286.4 2395.52  5292.6 2396.75
#Mann=5,-1,0
  4658.5    0.07       0  4897.1    0.16       0  5024.4    0.07       0
  5028.4    0.16       0  5054.4    0.07       0
Bank Sta=5024.4,5028.4
Exp/Cntr=0.3,0.1

Type RM Length L Ch R = 1,934,215,215,215
BEGIN DESCRIPTION:
elmc206
END DESCRIPTION:
XS GIS Cut Line= 3
      1469160.20      6784859.88      1469384.91      6784488.23
      1469635.82      6784182.90
#Sta/Elev= 30
  4565.7 2391.66  4602.1 2388.78  4701.4 2383.17  4738.3 2381.94  4781.0 2377.54
  4825.0 2374.99  4871.9 2373.75  4883.4 2373.63  4918.8 2370.95  4928.4 2369.20
  4934.3 2369.32  4949.8 2363.90  4955.6 2364.05  4971.1 2360.90  4990.5 2360.37
  4990.7 2359.87  4994.5 2360.37  5036.1 2362.42  5056.9 2361.99  5085.6 2372.91
  5092.1 2376.53  5099.9 2378.46  5106.4 2382.26  5120.8 2385.43  5227.7 2391.98
  5247.1 2393.87  5270.7 2395.66  5277.2 2396.92  5351.0 2401.10  5395.2 2403.14
#Mann=7,-1,0
  4565.7    0.16       0  4602.1    0.07       0  4871.9    0.16       0
  4990.5    0.07       0  4994.5    0.16       0  5247.1    0.07       0
  5351.0    0.16       0
Bank Sta=4990.5,4994.5
Exp/Cntr=0.3,0.1

Type RM Length L Ch R = 1,719,221,221,221
BEGIN DESCRIPTION:
elmc247
END DESCRIPTION:
XS GIS Cut Line= 2
      1469260.98      6784876.13      1469724.39      6784441.99
#Sta/Elev= 30
  4600.3 2386.48  4693.8 2382.12  4743.1 2374.93  4771.4 2371.84  4821.2 2367.90
  4869.6 2366.10  4898.9 2364.94  4941.4 2361.92  4948.4 2361.38  4955.6 2359.80
  4983.9 2358.61  4996.1 2356.52  4996.3 2356.02  5000.1 2356.52  5004.9 2357.13
  5019.1 2362.54  5033.2 2369.47  5047.4 2378.76  5054.7 2382.57  5068.9 2386.13
  5104.1 2390.02  5153.9 2392.96  5160.7 2394.25  5174.9 2394.39  5181.7 2395.66
  5189.1 2395.69  5195.9 2397.50  5203.2 2396.95  5210.1 2398.17  5235.3 2399.64
#Mann=4,-1,0
  4600.3    0.07       0  4869.6    0.16       0  4996.1    0.07       0
  5000.1    0.16       0
Bank Sta=4996.1,5000.1
Exp/Cntr=0.3,0.1

Type RM Length L Ch R = 1,498,174,174,174
BEGIN DESCRIPTION:
elmc205
END DESCRIPTION:
XS GIS Cut Line= 3
      1469323.38      6784957.11      1469656.31      6784789.82
      1469965.77      6784505.70
#Sta/Elev= 30
  4627.4 2388.17  4663.6 2385.37  4674.0 2385.42  4708.3 2383.34  4725.0 2383.25
  4808.3 2375.48  4830.7 2371.20  4842.2 2367.64  4853.0 2365.36  4859.0 2362.20
  4884.3 2358.88  4953.9 2358.51  5012.3 2354.87  5012.6 2354.37  5016.1 2354.37
  5016.3 2354.87  5050.1 2356.92  5064.3 2361.88  5127.8 2378.83  5134.6 2383.61
  5148.7 2385.05  5170.3 2389.03  5212.9 2392.56  5219.7 2393.68  5227.0 2393.80
  5233.8 2395.24  5269.6 2398.92  5375.6 2403.95  5396.6 2405.91  5420.1 2406.81
#Mann=4,-1,0
  4627.4    0.07       0  4884.3    0.16       0  5012.3    0.07       0
  5016.3    0.16       0
Bank Sta=5012.3,5016.3
Exp/Cntr=0.3,0.1

Type RM Length L Ch R = 1,324,267,267,267
BEGIN DESCRIPTION:
elmc246
END DESCRIPTION:
XS GIS Cut Line= 4
      1469407.67      6785010.56      1469693.67      6784959.22
      1469813.44      6784871.22      1469998.48      6784652.10
#Sta/Elev= 30
  4684.8 2385.70  4712.6 2383.84  4722.6 2380.98  4727.7 2381.57  4732.9 2377.31
  4743.0 2373.87  4773.5 2368.01  4814.2 2364.79  4854.8 2363.68  4893.9 2358.80
  4915.4 2357.38  4957.7 2356.00  4973.5 2352.43  4982.6 2352.27  4982.8 2351.77
  4986.6 2352.27  5034.7 2354.86  5120.4 2355.47  5141.3 2356.75  5169.6 2361.90
  5177.3 2365.33  5183.9 2366.27  5191.6 2370.71  5198.2 2371.77  5205.9 2376.27
  5212.5 2377.87  5219.8 2383.04  5226.8 2385.27  5339.9 2398.97  5410.8 2402.33
#Mann=4,-1,0
  4684.8    0.07       0  4915.4    0.16       0  4982.6    0.07       0
  4986.6    0.16       0
Bank Sta=4982.6,4986.6
Exp/Cntr=0.3,0.1

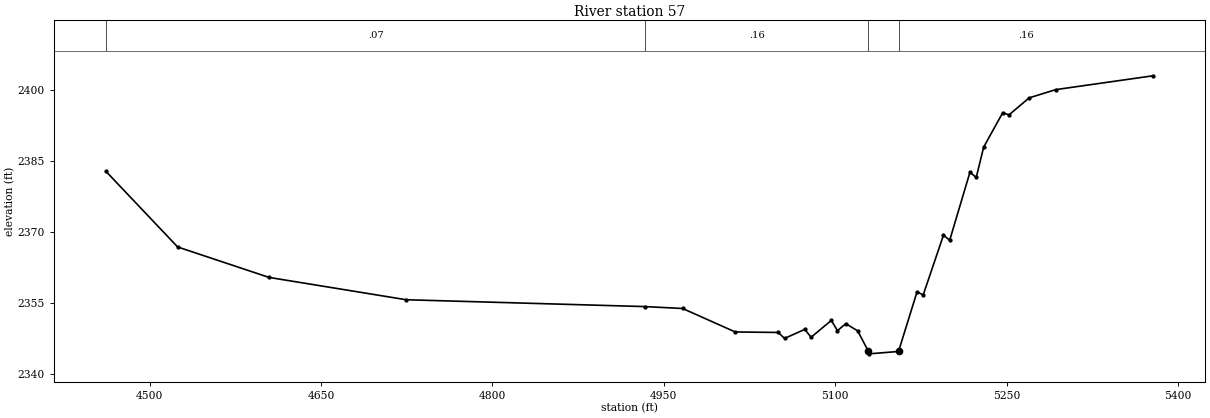
Type RM Length L Ch R = 1,57,0,0,0
BEGIN DESCRIPTION:
elmc245
END DESCRIPTION:
XS GIS Cut Line= 4
      1469422.38      6785076.56      1469845.22      6785076.56
      1469984.56      6785013.00      1470123.78      6784702.80
#Sta/Elev= 30
  4462.0 2382.83  4524.6 2366.87  4604.6 2360.43  4724.6 2355.71  4933.7 2354.26
  4966.4 2353.86  5012.4 2348.90  5050.1 2348.79  5055.6 2347.53  5073.3 2349.45
  5078.8 2347.77  5096.5 2351.34  5101.9 2349.17  5109.2 2350.66  5119.6 2349.12
  5129.0 2344.77  5129.5 2344.27  5155.3 2344.77  5171.5 2357.38  5176.9 2356.73
  5194.6 2369.35  5200.1 2368.30  5217.8 2382.68  5223.3 2381.57  5229.8 2387.99
  5246.5 2395.28  5251.9 2394.79  5269.6 2398.40  5292.8 2400.14  5378.0 2403.07
#Mann=4,-1,0
  4462.0    0.07       0  4933.7    0.16       0  5129.0    0.07       0
  5155.3    0.16       0
Bank Sta=5129,5155.3
Exp/Cntr=0.3,0.1

Chan Stop Cuts=-1