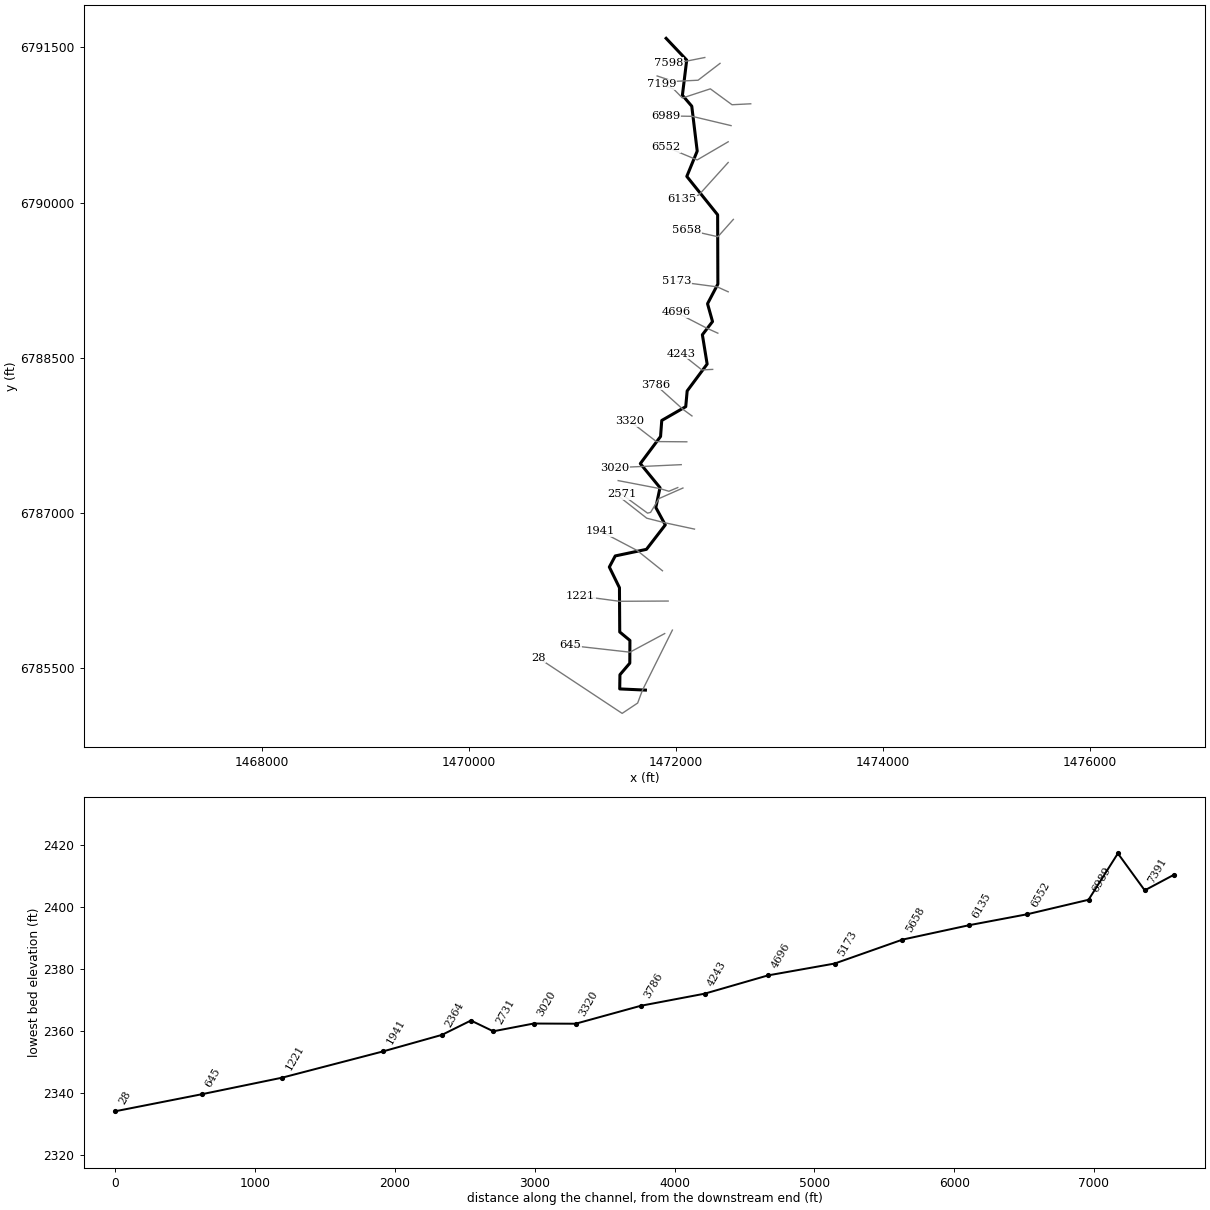
--- Elm 10.prj (project) ---

Proj Title=Elm 10 Base Level Engineering
Current Plan=p01
Default Exp/Contr=0.3,0.1
English Units
Geom File=g01
Flow File=f01
Plan File=p01
BEGIN DESCRIPTION:
Elm 10
END DESCRIPTION:

--- Elm 10.p01 (plan) ---

Plan Title=Multiple Run
Short Identifier=Multiple
Geom File=g01
Flow File=f01
Subcritical Flow
K Sum by GR= 0
Std Step Tol= 0.01
Critical Tol= 0.01
Num of Std Step Trials= 20
Max Error Tol= 0.3
Flow Tol Ratio= 0.001
Split Flow NTrial= 30
Split Flow Tol= 0.02
Split Flow Ratio= 0.02
Log Output Level= 0
Friction Slope Method= 1
Unsteady Friction Slope Method= 2
Unsteady Bridges Friction Slope Method= 1
Parabolic Critical Depth
Global Vel Dist=  1 , 1 , 1
Global Log Level= 0
CheckData=True
Encroach Param= -1, 0, 0, 0
BEGIN DESCRIPTION:
Multiple Run
END DESCRIPTION:

--- Elm 10.f01 (steady flow) ---

Flow Title=Multiple
Number of Profiles=7
Profile Names=10-year,25-year,50-year,1pct_min,100-year,1pct_plu,500-year
River Rch & RM= Elm 10,Reach-1,7598
     219     302     370     281     451     620     676
River Rch & RM= Elm 10,Reach-1,5173
     371     526     657     509     815    1120    1270
Boundary for River Rch & Prof#=Elm 10,Reach-1,1
Up Type=0
Dn Type=3
Dn Slope=0.005
Boundary for River Rch & Prof#=Elm 10,Reach-1,2
Up Type=0
Dn Type=3
Dn Slope=0.005
Boundary for River Rch & Prof#=Elm 10,Reach-1,3
Up Type=0
Dn Type=3
Dn Slope=0.005
Boundary for River Rch & Prof#=Elm 10,Reach-1,4
Up Type=0
Dn Type=3
Dn Slope=0.005
Boundary for River Rch & Prof#=Elm 10,Reach-1,5
Up Type=0
Dn Type=3
Dn Slope=0.005
Boundary for River Rch & Prof#=Elm 10,Reach-1,6
Up Type=0
Dn Type=3
Dn Slope=0.005
Boundary for River Rch & Prof#=Elm 10,Reach-1,7
Up Type=0
Dn Type=3
Dn Slope=0.005

--- Elm 10.g01 (geometry) ---

Geom Title=Existing Conditions

River Reach=Elm 10,Reach-1
Reach XY= 30
      1471905.00      6791588.00      1472104.03      6791377.71
      1472062.36      6791037.92      1472152.93      6790932.15
      1472205.50      6790498.17      1472105.02      6790253.41
      1472402.94      6789882.15      1472405.21      6789212.91
      1472305.37      6789022.73      1472353.53      6788850.13
      1472255.49      6788722.80      1472301.53      6788439.50
      1472108.41      6788179.56      1472094.67      6788027.83
      1471862.81      6787894.21      1471851.24      6787739.56
      1471655.55      6787477.36      1471845.87      6787244.74
      1471805.49      6787053.22      1471896.98      6786884.69
      1471714.80      6786648.48      1471413.31      6786584.85
      1471356.07      6786477.47      1471453.96      6786277.56
      1471456.65      6785849.83      1471555.07      6785768.12
      1471553.94      6785548.44      1471458.54      6785436.52
      1471456.47      6785299.49      1471705.00      6785288.00

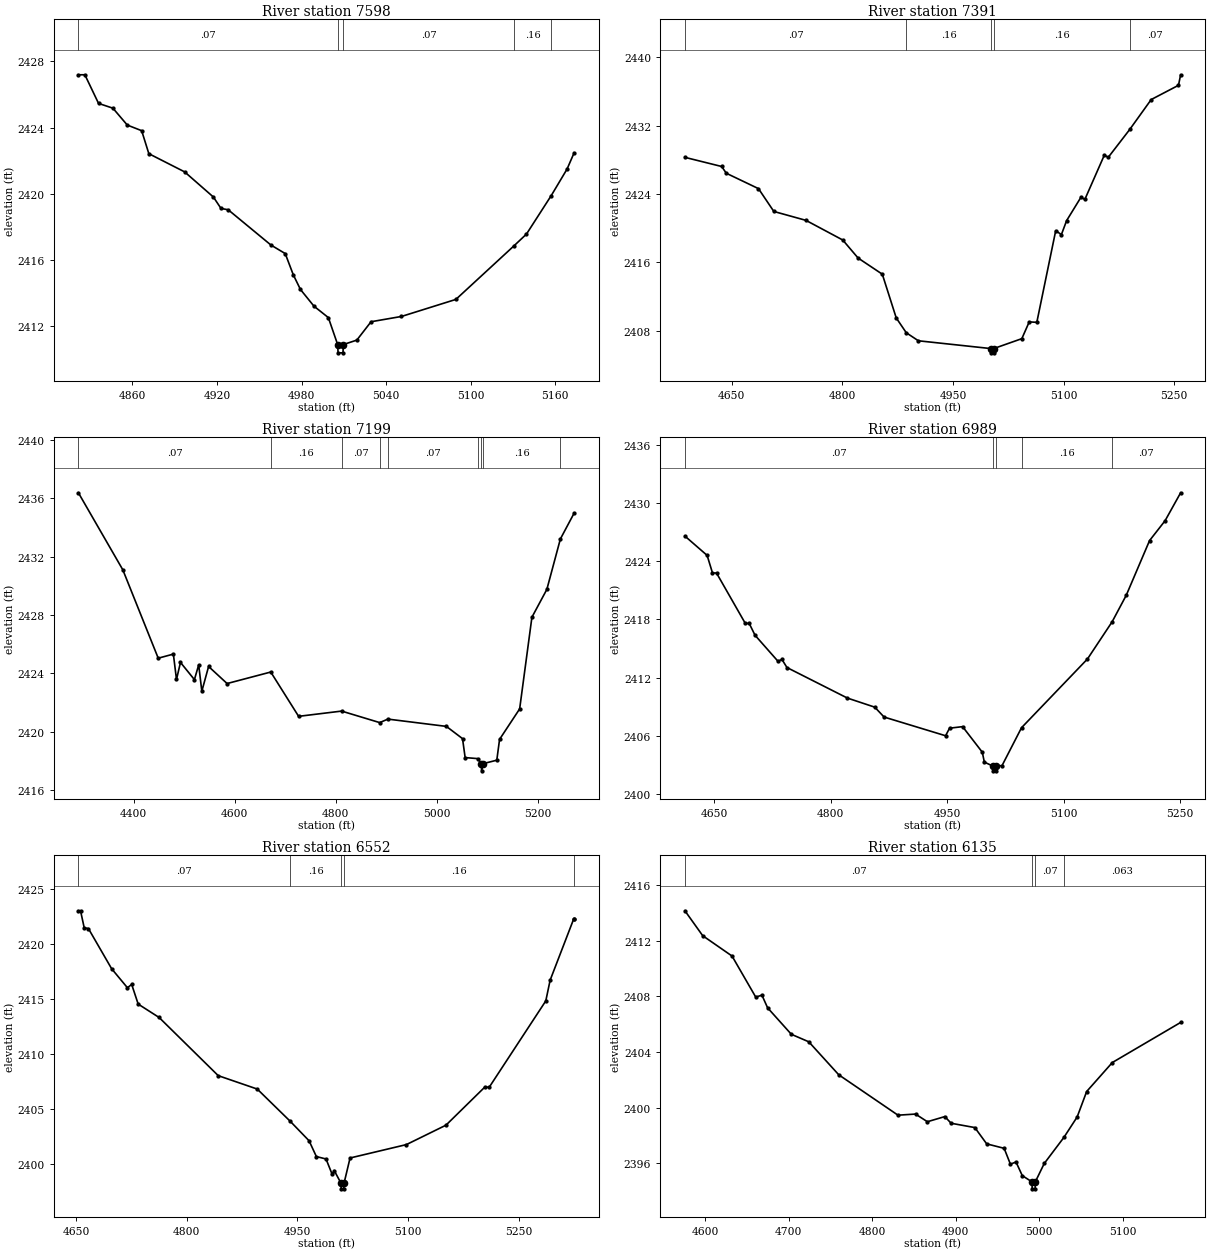
Type RM Length L Ch R = 1,7598,207,207,207
BEGIN DESCRIPTION:
347
END DESCRIPTION:
XS GIS Cut Line= 3
      1472279.01      6791402.71      1472092.99      6791365.91
      1471931.33      6791352.90
#Sta/Elev= 30
  4821.6 2427.19  4826.2 2427.19  4835.9 2425.46  4846.1 2425.17  4856.3 2424.15
  4866.5 2423.81  4871.6 2422.42  4897.0 2421.32  4917.4 2419.80  4922.8 2419.11
  4927.9 2419.03  4958.2 2416.90  4968.4 2416.38  4974.1 2415.10  4979.2 2414.21
  4988.8 2413.20  4999.0 2412.51  5005.6 2410.88  5005.9 2410.38  5009.4 2410.38
  5009.6 2410.88  5019.2 2411.15  5029.3 2412.26  5050.9 2412.58  5089.5 2413.61
  5130.5 2416.83  5139.6 2417.56  5157.2 2419.89  5168.4 2421.49  5173.4 2422.47
#Mann=5,-1,0
  4821.6    0.07       0  5005.6    0.07       0  5009.6    0.07       0
  5130.5    0.16       0  5157.2    0.07       0
Bank Sta=5005.6,5009.6
Exp/Cntr=0.3,0.1

Type RM Length L Ch R = 1,7391,192,192,192
BEGIN DESCRIPTION:
757
END DESCRIPTION:
XS GIS Cut Line= 4
      1472426.10      6791345.95      1472213.83      6791183.17
      1471978.15      6791171.45      1471818.34      6791224.29
#Sta/Elev= 30
  4586.8 2428.28  4636.6 2427.21  4642.9 2426.42  4686.5 2424.62  4707.3 2421.95
  4750.8 2420.91  4800.7 2418.61  4821.5 2416.50  4854.3 2414.61  4873.2 2409.49
  4886.8 2407.76  4903.2 2406.82  5001.3 2405.91  5001.6 2405.41  5005.1 2405.41
  5005.3 2405.91  5043.4 2407.07  5053.4 2409.03  5063.7 2408.98  5089.3 2419.70
  5097.0 2419.24  5104.1 2420.88  5123.5 2423.61  5128.8 2423.36  5155.2 2428.54
  5160.5 2428.28  5189.6 2431.54  5218.7 2435.04  5255.7 2436.71  5258.6 2437.94
#Mann=5,-1,0
  4586.8    0.07       0  4886.8    0.16       0  5001.3    0.07       0
  5005.3    0.16       0  5189.6    0.07       0
Bank Sta=5001.3,5005.3
Exp/Cntr=0.3,0.1

Type RM Length L Ch R = 1,7199,210,210,210
BEGIN DESCRIPTION:
756
END DESCRIPTION:
XS GIS Cut Line= 6
      1472722.96      6790955.30      1472541.96      6790946.19
      1472332.32      6791099.83      1472062.79      6791011.29
      1471979.46      6791095.93      1471860.56      6791143.23
#Sta/Elev= 30
  4290.2 2436.39  4378.3 2431.10  4448.4 2425.04  4478.4 2425.32  4484.6 2423.58
  4492.5 2424.75  4520.1 2423.57  4528.6 2424.58  4534.8 2422.77  4548.2 2424.47
  4584.9 2423.30  4671.4 2424.09  4726.6 2421.05  4811.8 2421.41  4887.3 2420.62
  4903.5 2420.86  5019.4 2420.36  5051.4 2419.52  5056.6 2418.22  5081.1 2418.15
  5088.9 2417.81  5089.1 2417.31  5092.9 2417.81  5119.3 2418.04  5124.8 2419.47
  5164.6 2421.56  5188.9 2427.85  5218.5 2429.76  5245.3 2433.22  5272.5 2434.99
#Mann=9,-1,0
  4290.2    0.07       0  4671.4    0.16       0  4811.8    0.07       0
  4887.3    0.16       0  4903.5    0.07       0  5081.1    0.16       0
  5088.9    0.07       0  5092.9    0.16       0  5245.3    0.07       0
Bank Sta=5088.9,5092.9
Exp/Cntr=0.3,0.1

Type RM Length L Ch R = 1,6989,437,437,437
BEGIN DESCRIPTION:
346
END DESCRIPTION:
XS GIS Cut Line= 3
      1472532.85      6790744.36      1472155.50      6790834.21
      1471905.02      6790838.00
#Sta/Elev= 30
  4612.1 2426.59  4640.7 2424.60  4647.6 2422.79  4652.8 2422.78  4689.8 2417.59
  4694.9 2417.58  4702.4 2416.36  4731.9 2413.68  4737.1 2413.86  4743.5 2413.03
  4821.3 2409.88  4856.6 2408.94  4868.6 2407.92  4947.8 2405.99  4952.9 2406.77
  4969.7 2406.93  4995.1 2404.29  4997.7 2403.27  5008.5 2402.87  5008.7 2402.37
  5012.2 2402.37  5012.5 2402.87  5020.5 2402.91  5045.6 2406.82  5130.5 2413.91
  5162.3 2417.75  5180.5 2420.49  5210.5 2426.13  5230.5 2428.18  5250.5 2431.06
#Mann=5,-1,0
  4612.1    0.07       0  5008.5    0.07       0  5012.5    0.07       0
  5045.6    0.16       0  5162.3    0.07       0
Bank Sta=5008.5,5012.5
Exp/Cntr=0.3,0.1

Type RM Length L Ch R = 1,6552,417,417,417
BEGIN DESCRIPTION:
345
END DESCRIPTION:
XS GIS Cut Line= 3
      1472505.01      6790588.00      1472205.32      6790412.89
      1471905.03      6790537.99
#Sta/Elev= 30
  4652.9 2423.05  4655.8 2423.05  4660.8 2421.50  4666.5 2421.43  4698.0 2417.77
  4719.4 2416.04  4725.2 2416.34  4734.0 2414.55  4762.4 2413.33  4842.6 2408.03
  4895.5 2406.81  4940.3 2403.87  4965.8 2402.10  4975.7 2400.66  4988.8 2400.44
  4997.2 2399.03  4999.9 2399.39  5009.2 2398.22  5009.4 2397.72  5012.9 2397.72
  5013.2 2398.22  5021.4 2400.53  5097.8 2401.75  5151.5 2403.52  5204.5 2407.01
  5210.0 2406.96  5286.9 2414.84  5292.8 2416.73  5324.5 2422.26  5325.3 2422.26
#Mann=5,-1,0
  4652.9    0.07       0  4940.3    0.16       0  5009.2    0.07       0
  5013.2    0.16       0  5324.5    0.07       0
Bank Sta=5009.2,5013.2
Exp/Cntr=0.3,0.1

Type RM Length L Ch R = 1,6135,477,477,477
BEGIN DESCRIPTION:
344
END DESCRIPTION:
XS GIS Cut Line= 3
      1472504.97      6790387.97      1472220.67      6790073.28
      1472054.99      6790038.00
#Sta/Elev= 30
  4575.9 2414.15  4597.2 2412.36  4632.3 2410.90  4660.7 2407.95  4668.1 2408.09
  4674.9 2407.18  4703.3 2405.28  4724.2 2404.74  4760.1 2402.37  4831.0 2399.47
  4852.0 2399.55  4866.2 2399.00  4887.1 2399.37  4894.6 2398.89  4923.0 2398.58
  4937.2 2397.41  4958.1 2397.09  4965.6 2395.95  4972.3 2396.11  4979.8 2395.13
  4991.4 2394.68  4991.7 2394.18  4995.2 2394.18  4995.4 2394.68  5006.1 2396.00
  5029.6 2397.87  5045.5 2399.34  5056.9 2401.17  5087.6 2403.25  5169.4 2406.13
#Mann=4,-1,0
  4575.9    0.07       0  4991.4    0.07       0  4995.4    0.07       0
  5029.6   0.063       0
Bank Sta=4991.4,4995.4
Exp/Cntr=0.3,0.1

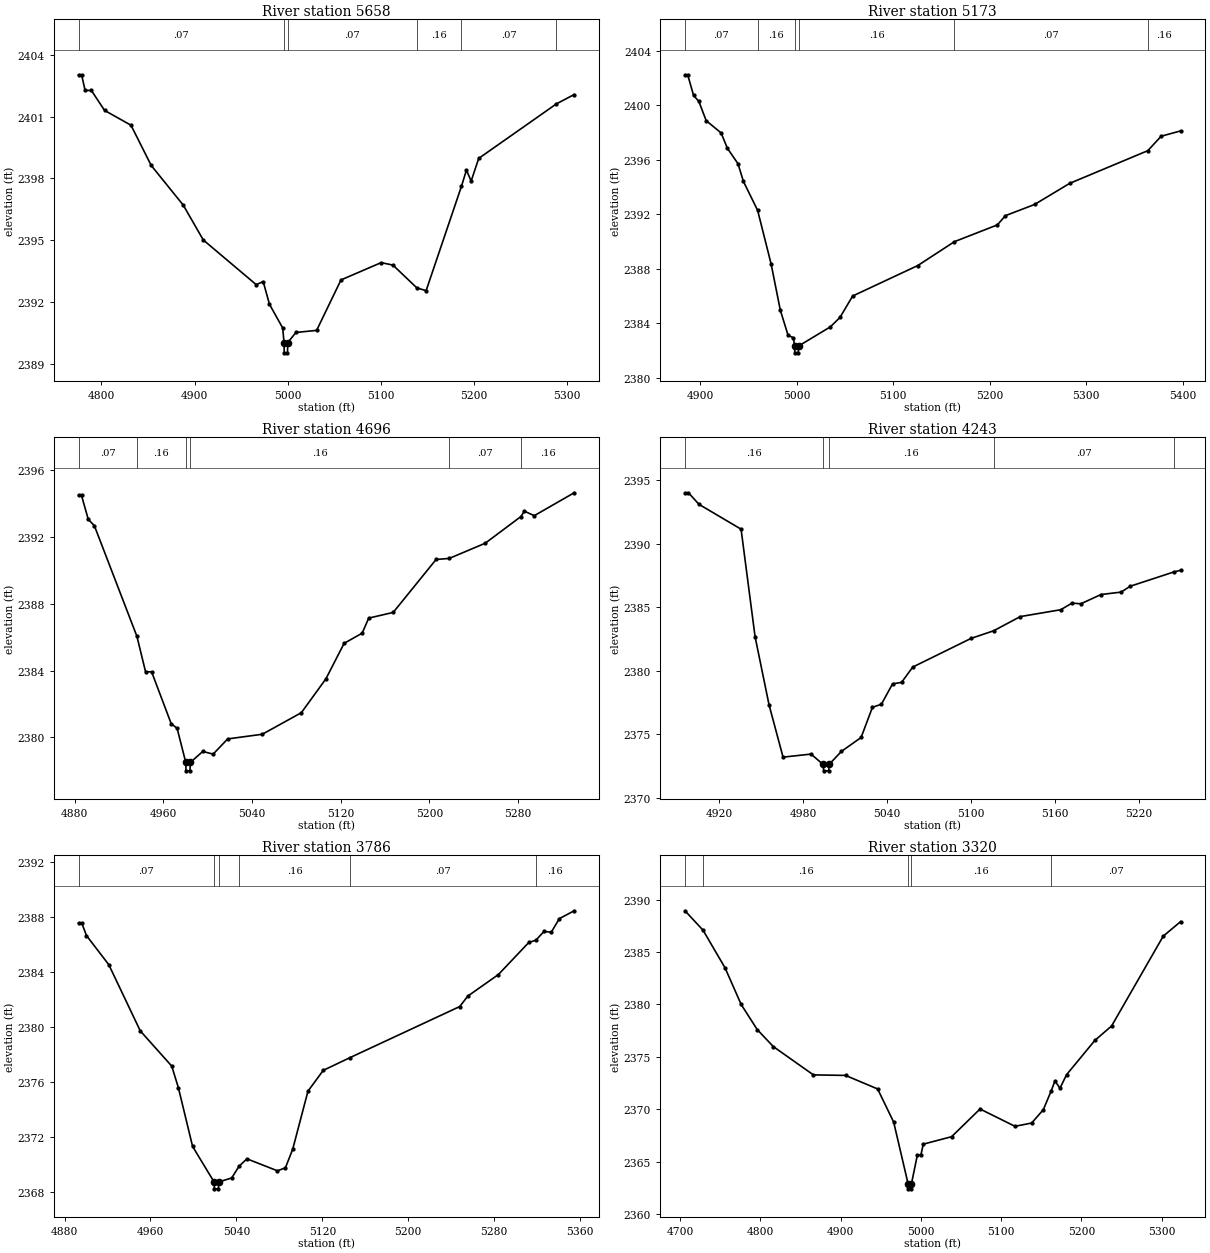
Type RM Length L Ch R = 1,5658,485,485,485
BEGIN DESCRIPTION:
343
END DESCRIPTION:
XS GIS Cut Line= 3
      1472554.97      6789837.96      1472405.41      6789670.26
      1472104.95      6789738.01
#Sta/Elev= 30
  4775.3 2403.03  4778.6 2403.03  4782.4 2402.27  4789.1 2402.27  4803.3 2401.30
  4831.7 2400.58  4853.4 2398.63  4887.9 2396.70  4909.4 2395.01  4966.3 2392.84
  4973.8 2392.99  4980.5 2391.89  4994.7 2390.74  4996.2 2390.03  4996.4 2389.53
  4999.9 2389.53  5000.2 2390.03  5009.0 2390.52  5031.2 2390.62  5057.4 2393.07
  5100.6 2393.91  5113.2 2393.79  5139.0 2392.68  5148.9 2392.55  5186.9 2397.62
  5192.2 2398.40  5197.3 2397.87  5205.4 2398.97  5289.0 2401.62  5308.0 2402.07
#Mann=6,-1,0
  4775.3    0.07       0  4996.2    0.07       0  5000.2    0.07       0
  5139.0    0.16       0  5186.9    0.07       0  5289.0    0.16       0
Bank Sta=4996.2,5000.2
Exp/Cntr=0.3,0.1

Type RM Length L Ch R = 1,5173,477,477,477
BEGIN DESCRIPTION:
342
END DESCRIPTION:
XS GIS Cut Line= 3
      1472505.04      6789137.98      1472399.29      6789185.65
      1472004.95      6789238.01
#Sta/Elev= 30
  4884.0 2402.23  4886.8 2402.23  4892.9 2400.72  4898.4 2400.27  4906.0 2398.86
  4921.5 2397.96  4927.9 2396.84  4938.9 2395.71  4944.6 2394.40  4959.3 2392.28
  4973.3 2388.34  4982.8 2384.96  4990.9 2383.10  4996.4 2382.93  4997.6 2382.32
  4997.8 2381.82  5001.4 2381.82  5001.7 2382.32  5034.6 2383.72  5044.7 2384.42
  5057.8 2385.99  5125.4 2388.23  5163.3 2389.98  5207.8 2391.21  5216.2 2391.89
  5246.4 2392.71  5282.8 2394.26  5363.8 2396.66  5377.6 2397.72  5397.8 2398.11
#Mann=6,-1,0
  4884.0    0.07       0  4959.3    0.16       0  4997.6    0.07       0
  5001.7    0.16       0  5163.3    0.07       0  5363.8    0.16       0
Bank Sta=4997.6,5001.7
Exp/Cntr=0.3,0.1

Type RM Length L Ch R = 1,4696,453,453,453
BEGIN DESCRIPTION:
341
END DESCRIPTION:
XS GIS Cut Line= 3
      1472404.99      6788738.00      1472298.79      6788786.14
      1472005.02      6788937.99
#Sta/Elev= 30
  4883.4 2394.48  4886.1 2394.48  4892.2 2393.05  4897.7 2392.67  4936.1 2386.05
  4943.9 2383.93  4949.4 2383.92  4967.0 2380.83  4972.4 2380.54  4980.2 2378.50
  4980.4 2378.00  4984.0 2378.00  4984.3 2378.50  4995.5 2379.16  5004.9 2379.00
  5018.0 2379.91  5049.3 2380.19  5084.5 2381.48  5106.6 2383.50  5123.1 2385.63
  5139.4 2386.24  5145.3 2387.14  5167.4 2387.48  5206.1 2390.65  5217.9 2390.71
  5250.4 2391.62  5282.7 2393.22  5285.7 2393.54  5294.7 2393.27  5330.7 2394.64
#Mann=6,-1,0
  4883.4    0.07       0  4936.1    0.16       0  4980.2    0.07       0
  4984.3    0.16       0  5217.9    0.07       0  5282.7    0.16       0
Bank Sta=4980.2,4984.3
Exp/Cntr=0.3,0.1

Type RM Length L Ch R = 1,4243,457,457,457
BEGIN DESCRIPTION:
340
END DESCRIPTION:
XS GIS Cut Line= 3
      1472355.03      6788388.00      1472250.86      6788382.65
      1472054.99      6788538.01
#Sta/Elev= 30
  4895.7 2394.03  4898.2 2394.03  4905.7 2393.12  4935.8 2391.16  4945.8 2382.69
  4955.8 2377.31  4965.8 2373.19  4985.8 2373.43  4994.5 2372.61  4994.8 2372.11
  4998.4 2372.11  4998.7 2372.61  5007.5 2373.64  5021.6 2374.74  5029.7 2377.12
  5036.1 2377.36  5044.1 2378.97  5050.5 2379.08  5058.5 2380.29  5100.2 2382.55
  5116.3 2383.15  5135.4 2384.27  5164.3 2384.81  5172.3 2385.33  5178.7 2385.28
  5193.1 2386.01  5207.5 2386.20  5213.9 2386.66  5245.5 2387.80  5250.0 2387.92
#Mann=5,-1,0
  4895.7    0.16       0  4994.5    0.07       0  4998.7    0.16       0
  5116.3    0.07       0  5245.5    0.16       0
Bank Sta=4994.5,4998.7
Exp/Cntr=0.3,0.1

Type RM Length L Ch R = 1,3786,466,466,466
BEGIN DESCRIPTION:
339
END DESCRIPTION:
XS GIS Cut Line= 3
      1472155.03      6787937.98      1472068.73      6788001.23
      1471805.01      6788237.99
#Sta/Elev= 30
  4893.0 2387.51  4896.1 2387.51  4900.4 2386.62  4921.2 2384.50  4950.5 2379.69
  4979.8 2377.13  4986.0 2375.55  4999.2 2371.29  5019.2 2368.71  5019.5 2368.21
  5023.2 2368.21  5023.5 2368.71  5035.6 2369.00  5042.5 2369.86  5049.8 2370.39
  5078.2 2369.52  5085.6 2369.74  5092.4 2371.09  5106.6 2375.31  5120.8 2376.82
  5145.8 2377.75  5247.9 2381.46  5255.4 2382.22  5283.8 2383.78  5312.2 2386.12
  5318.7 2386.28  5326.4 2386.92  5333.1 2386.86  5340.6 2387.85  5354.4 2388.42
#Mann=6,-1,0
  4893.0    0.07       0  5019.2    0.07       0  5023.5    0.07       0
  5042.5    0.16       0  5145.8    0.07       0  5318.7    0.16       0
Bank Sta=5019.2,5023.5
Exp/Cntr=0.3,0.1

Type RM Length L Ch R = 1,3320,300,300,300
BEGIN DESCRIPTION:
338
END DESCRIPTION:
XS GIS Cut Line= 3
      1472105.03      6787688.00      1471811.14      6787690.17
      1471555.04      6787887.97
#Sta/Elev= 30
  4706.1 2388.93  4728.6 2387.08  4756.1 2383.48  4776.1 2380.00  4796.1 2377.61
  4816.1 2375.99  4866.1 2373.29  4906.1 2373.24  4946.1 2371.95  4966.1 2368.79
  4984.0 2362.93  4984.2 2362.43  4988.0 2362.43  4988.3 2362.93  4995.6 2365.65
  5000.0 2365.65  5003.0 2366.69  5038.3 2367.40  5073.7 2370.04  5117.2 2368.39
  5138.0 2368.70  5152.5 2369.97  5162.5 2371.79  5167.0 2372.71  5173.3 2372.02
  5181.5 2373.31  5216.8 2376.58  5237.6 2377.95  5301.9 2386.51  5323.6 2387.90
#Mann=5,-1,0
  4706.1    0.07       0  4728.6    0.16       0  4984.0    0.07       0
  4988.3    0.16       0  5162.5    0.07       0
Bank Sta=4984,4988.3
Exp/Cntr=0.3,0.1

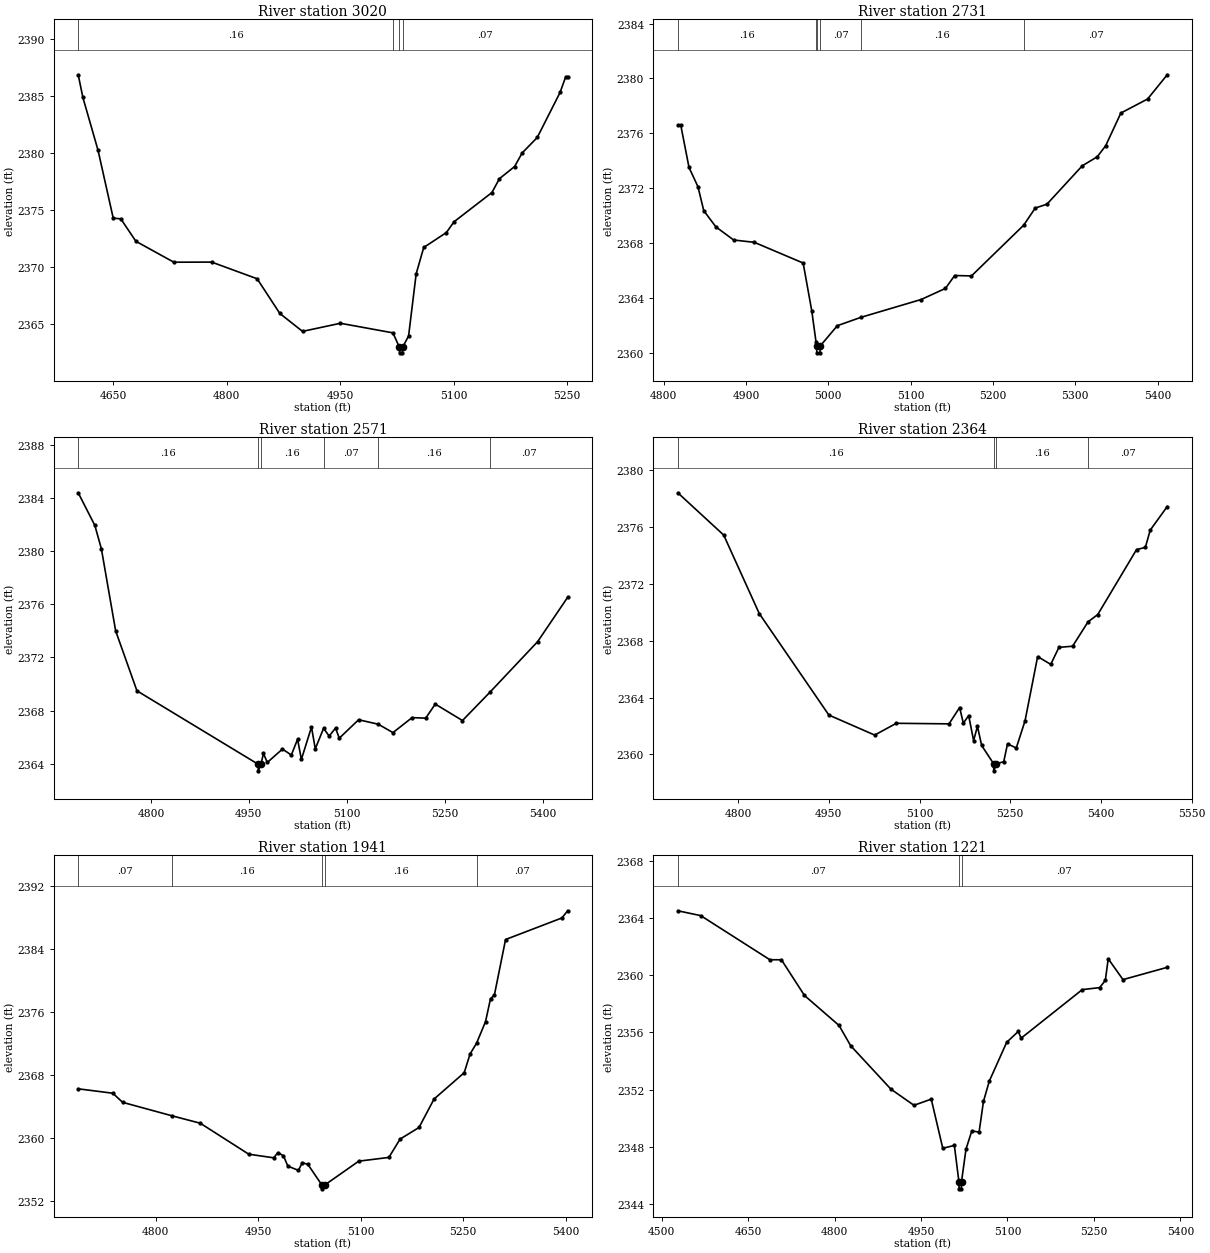
Type RM Length L Ch R = 1,3020,289,289,289
BEGIN DESCRIPTION:
337
END DESCRIPTION:
XS GIS Cut Line= 3
      1472051.22      6787467.13      1471655.55      6787448.64
      1471404.97      6787438.00
#Sta/Elev= 30
  4603.9 2386.85  4610.1 2384.86  4630.1 2380.24  4650.2 2374.29  4660.2 2374.23
  4680.2 2372.26  4730.3 2370.43  4780.3 2370.44  4840.4 2368.98  4870.4 2365.94
  4900.4 2364.37  4950.5 2365.08  5019.9 2364.24  5028.4 2362.99  5028.7 2362.49
  5032.5 2362.49  5032.8 2362.99  5040.6 2363.97  5050.6 2369.41  5060.6 2371.72
  5090.6 2373.03  5100.6 2373.97  5150.7 2376.53  5160.7 2377.75  5180.7 2378.81
  5190.7 2380.00  5210.7 2381.36  5240.8 2385.30  5248.3 2386.68  5250.8 2386.68
#Mann=4,-1,0
  4603.9    0.16       0  5019.9    0.07       0  5028.4    0.07       0
  5032.8    0.07       0
Bank Sta=5028.4,5032.8
Exp/Cntr=0.3,0.1

Type RM Length L Ch R = 1,2731,160,160,160
BEGIN DESCRIPTION:
755
END DESCRIPTION:
XS GIS Cut Line= 4
      1472017.59      6787245.79      1471931.82      6787209.97
      1471848.27      6787234.93      1471441.54      6787313.02
#Sta/Elev= 30
  4817.3 2376.59  4820.9 2376.59  4830.9 2373.51  4841.8 2372.10  4848.8 2370.36
  4863.5 2369.18  4885.1 2368.22  4910.2 2368.05  4969.5 2366.54  4980.0 2363.04
  4985.2 2360.75  4985.8 2360.49  4986.1 2359.99  4989.9 2359.99  4990.2 2360.49
  5011.0 2361.97  5039.7 2362.58  5112.8 2363.88  5142.3 2364.69  5153.5 2365.63
  5173.9 2365.60  5237.3 2369.30  5251.3 2370.55  5265.5 2370.83  5308.4 2373.63
  5326.6 2374.29  5336.8 2375.09  5355.3 2377.48  5387.7 2378.50  5411.6 2380.27
#Mann=6,-1,0
  4817.3    0.16       0  4985.2    0.07       0  4985.8    0.07       0
  4990.2    0.07       0  5039.7    0.16       0  5237.3    0.07       0
Bank Sta=4985.8,4990.2
Exp/Cntr=0.3,0.1

Type RM Length L Ch R = 1,2571,207,207,207
BEGIN DESCRIPTION:
754
END DESCRIPTION:
XS GIS Cut Line= 5
      1472067.48      6787241.44      1471836.34      6787139.44
      1471754.96      6787005.98      1471725.66      6786998.38
      1471475.01      6787181.76
#Sta/Elev= 30
  4688.6 2384.41  4714.1 2381.95  4724.1 2380.19  4746.0 2374.00  4778.6 2369.49
  4964.2 2363.96  4964.5 2363.46  4968.6 2363.96  4972.4 2364.77  4978.3 2364.09
  5001.5 2365.10  5015.1 2364.65  5024.7 2365.84  5030.5 2364.32  5046.0 2366.76
  5051.8 2365.12  5064.5 2366.66  5073.1 2366.08  5082.8 2366.68  5088.6 2365.92
  5118.2 2367.31  5148.4 2366.97  5170.8 2366.34  5200.1 2367.47  5221.0 2367.43
  5235.6 2368.49  5277.3 2367.25  5319.7 2369.40  5392.4 2373.19  5438.4 2376.53
#Mann=6,-1,0
  4688.6    0.16       0  4964.2    0.07       0  4968.6    0.16       0
  5064.5    0.07       0  5148.4    0.16       0  5319.7    0.07       0
Bank Sta=4964.2,4968.6
Exp/Cntr=0.3,0.1

Type RM Length L Ch R = 1,2364,423,423,423
BEGIN DESCRIPTION:
336
END DESCRIPTION:
XS GIS Cut Line= 4
      1472179.25      6786844.29      1471886.18      6786906.98
      1471718.06      6786949.55      1471453.34      6787156.77
#Sta/Elev= 30
  4700.3 2378.43  4776.2 2375.45  4835.0 2369.92  4950.1 2362.77  5025.8 2361.36
  5061.6 2362.19  5148.8 2362.15  5166.3 2363.30  5172.4 2362.20  5181.3 2362.73
  5189.4 2360.97  5195.8 2361.98  5202.7 2360.63  5222.5 2359.34  5222.8 2358.84
  5227.0 2359.34  5239.2 2359.48  5245.5 2360.74  5260.0 2360.45  5274.5 2362.37
  5295.3 2366.89  5317.0 2366.34  5330.5 2367.54  5353.1 2367.62  5378.7 2369.34
  5394.7 2369.85  5458.9 2374.43  5473.4 2374.58  5481.5 2375.80  5509.6 2377.46
#Mann=4,-1,0
  4700.3    0.16       0  5222.5    0.07       0  5227.0    0.16       0
  5378.7    0.07       0
Bank Sta=5222.5,5227
Exp/Cntr=0.3,0.1

Type RM Length L Ch R = 1,1941,720,720,720
BEGIN DESCRIPTION:
335
END DESCRIPTION:
XS GIS Cut Line= 3
      1471869.66      6786441.51      1471625.26      6786637.37
      1471268.69      6786824.74
#Sta/Elev= 30
  4686.8 2366.22  4737.4 2365.66  4751.8 2364.50  4823.4 2362.80  4865.4 2361.84
  4936.3 2357.90  4972.7 2357.44  4979.1 2358.10  4987.1 2357.69  4993.5 2356.38
  5009.0 2355.84  5014.7 2356.83  5022.9 2356.59  5043.2 2353.99  5043.5 2353.49
  5047.7 2353.99  5097.2 2357.01  5141.3 2357.49  5157.7 2359.82  5185.4 2361.30
  5207.4 2364.92  5251.5 2368.27  5260.1 2370.66  5269.5 2372.01  5282.7 2374.77
  5290.0 2377.70  5295.6 2378.13  5312.0 2385.22  5394.5 2387.97  5402.8 2388.88
#Mann=5,-1,0
  4686.8    0.07       0  4823.4    0.16       0  5043.2    0.07       0
  5047.7    0.16       0  5269.5    0.07       0
Bank Sta=5043.2,5047.7
Exp/Cntr=0.3,0.1

Type RM Length L Ch R = 1,1221,576,576,576
BEGIN DESCRIPTION:
753
END DESCRIPTION:
XS GIS Cut Line= 3
      1471924.83      6786148.78      1471454.53      6786146.38
      1471078.88      6786196.62
#Sta/Elev= 30
  4528.0 2364.52  4567.8 2364.18  4687.8 2361.09  4707.8 2361.09  4747.8 2358.59
  4807.8 2356.49  4827.8 2355.08  4897.8 2352.03  4937.8 2350.90  4967.8 2351.33
  4987.8 2347.89  5007.9 2348.09  5015.8 2345.55  5016.1 2345.05  5020.0 2345.05
  5020.3 2345.55  5028.1 2347.83  5038.2 2349.11  5050.8 2349.02  5058.4 2351.17
  5068.5 2352.59  5098.7 2355.31  5118.8 2356.07  5123.8 2355.60  5229.9 2359.00
  5260.1 2359.14  5269.9 2359.65  5274.9 2361.16  5300.5 2359.70  5377.3 2360.56
#Mann=3,-1,0
  4528.0    0.07       0  5015.8    0.07       0  5020.3    0.07       0
Bank Sta=5015.8,5020.3
Exp/Cntr=0.3,0.1

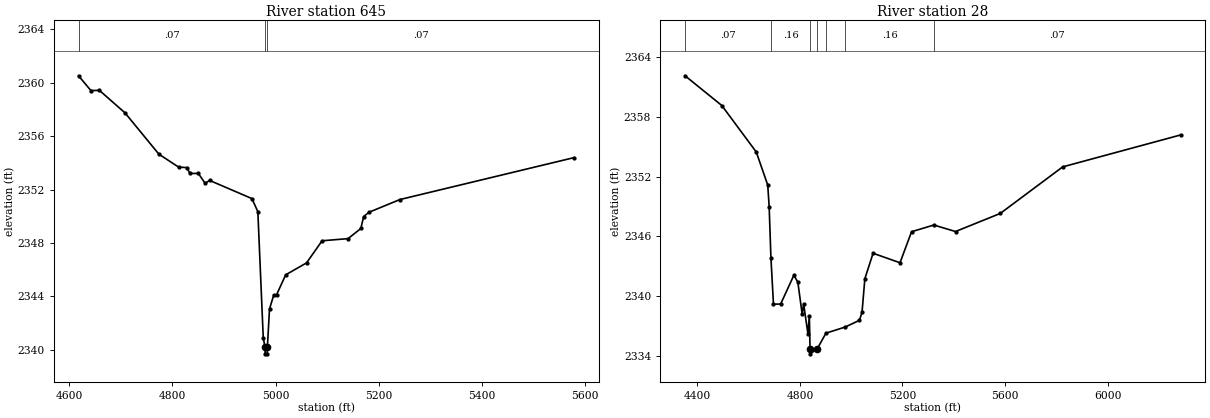
Type RM Length L Ch R = 1,645,617,617,617
BEGIN DESCRIPTION:
752
END DESCRIPTION:
XS GIS Cut Line= 3
      1471891.22      6785834.43      1471555.31      6785654.48
      1470979.72      6785719.23
#Sta/Elev= 30
  4618.1 2360.53  4642.2 2359.42  4658.5 2359.44  4708.0 2357.76  4773.8 2354.66
  4812.0 2353.69  4828.3 2353.65  4834.0 2353.21  4850.2 2353.22  4863.4 2352.48
  4872.2 2352.69  4954.1 2351.33  4965.6 2350.35  4976.1 2340.89  4979.5 2340.20
  4979.8 2339.70  4983.8 2339.70  4984.1 2340.20  4988.2 2343.06  4996.5 2344.12
  5001.8 2344.12  5019.6 2345.62  5059.9 2346.51  5090.1 2348.17  5140.4 2348.33
  5165.2 2349.09  5170.6 2349.98  5180.6 2350.30  5241.0 2351.26  5578.4 2354.40
#Mann=3,-1,0
  4618.1    0.07       0  4979.5    0.07       0  4984.1    0.07       0
Bank Sta=4979.5,4984.1
Exp/Cntr=0.3,0.1

Type RM Length L Ch R = 1,28,0,0,0
BEGIN DESCRIPTION:
334
END DESCRIPTION:
XS GIS Cut Line= 5
      1471965.61      6785868.01      1471675.28      6785284.95
      1471630.00      6785163.00      1471480.00      6785063.00
      1470669.93      6785599.26
#Sta/Elev= 30
  4352.0 2362.10  4495.4 2359.12  4629.8 2354.46  4674.5 2351.15  4680.1 2348.99
  4687.0 2343.84  4696.9 2339.21  4724.9 2339.22  4776.5 2342.11  4792.1 2341.40
  4808.9 2338.20  4814.5 2339.24  4831.3 2336.24  4836.8 2338.06  4839.6 2334.73
  4840.1 2334.23  4867.7 2334.73  4901.5 2336.30  4977.1 2336.92  5032.1 2337.59
  5042.3 2338.38  5053.4 2341.76  5085.4 2344.31  5190.5 2343.36  5235.6 2346.47
  5322.4 2347.14  5407.0 2346.49  5581.5 2348.30  5825.2 2352.97  6285.2 2356.17
#Mann=7,-1,0
  4352.0    0.07       0  4687.0    0.16       0  4839.6    0.07       0
  4867.7    0.16       0  4901.5    0.07       0  4977.1    0.16       0
  5322.4    0.07       0
Bank Sta=4839.6,4867.7
Exp/Cntr=0.3,0.1

Chan Stop Cuts=-1