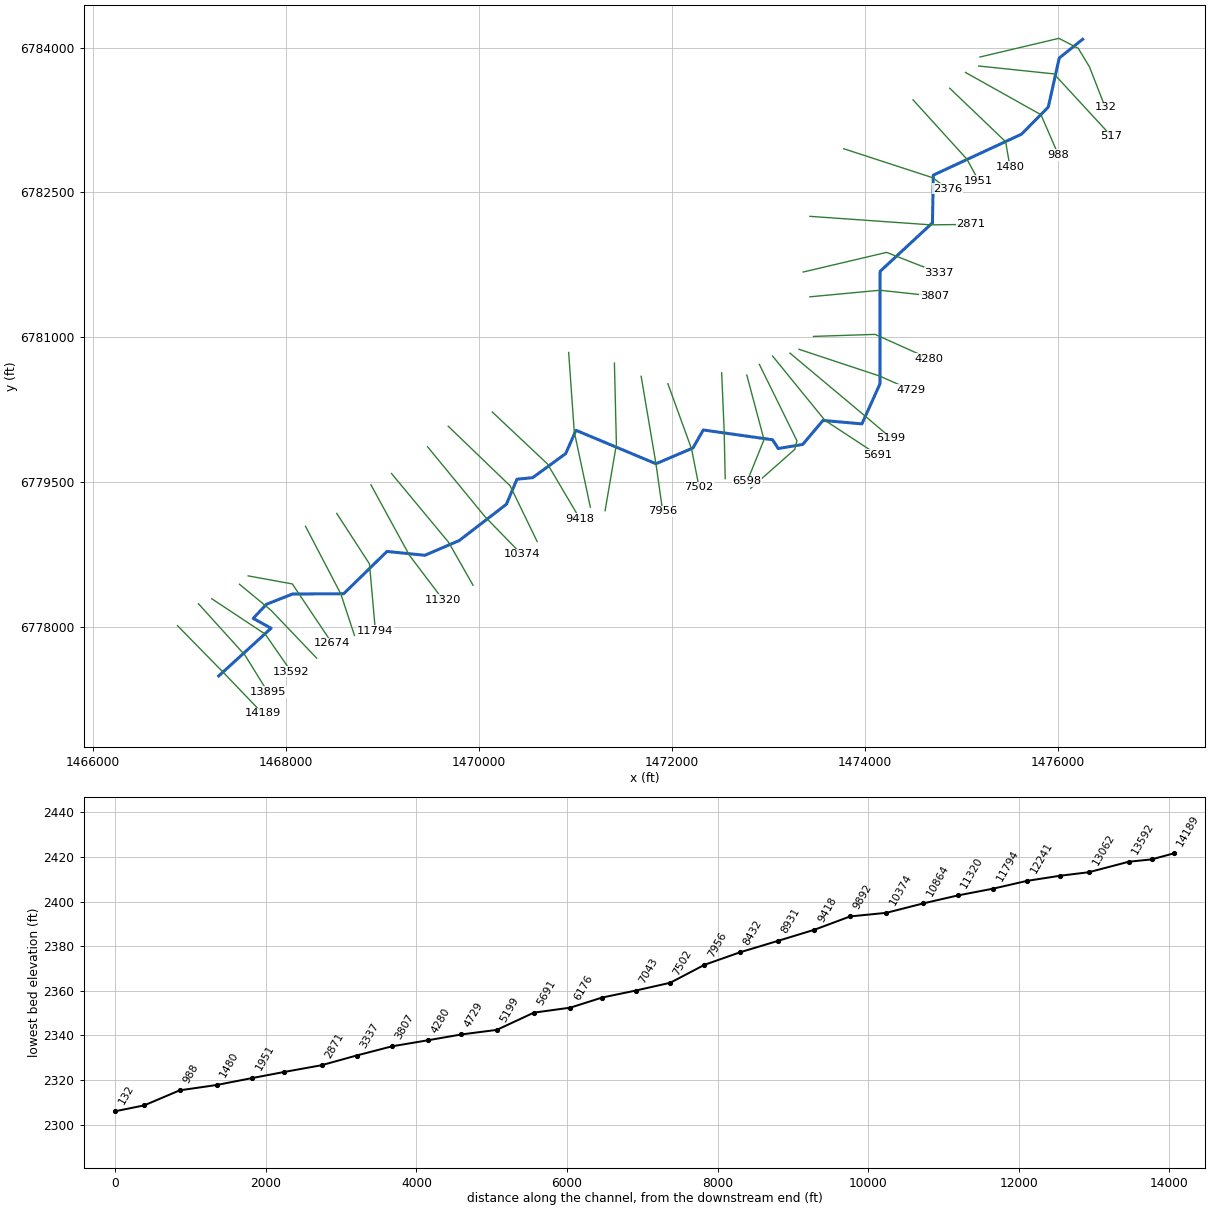
--- Elm 11.prj (project) ---

Proj Title=Elm 11 Base Level Engineering
Current Plan=p01
Default Exp/Contr=0.3,0.1
English Units
Geom File=g01
Flow File=f01
Plan File=p01
BEGIN DESCRIPTION:
Elm 11
END DESCRIPTION:

--- Elm 11.p01 (plan) ---

Plan Title=Multiple Run
Short Identifier=Multiple
Geom File=g01
Flow File=f01
Subcritical Flow
K Sum by GR= 0
Std Step Tol= 0.01
Critical Tol= 0.01
Num of Std Step Trials= 20
Max Error Tol= 0.3
Flow Tol Ratio= 0.001
Split Flow NTrial= 30
Split Flow Tol= 0.02
Split Flow Ratio= 0.02
Log Output Level= 0
Friction Slope Method= 1
Unsteady Friction Slope Method= 2
Unsteady Bridges Friction Slope Method= 1
Parabolic Critical Depth
Global Vel Dist=  1 , 1 , 1
Global Log Level= 0
CheckData=True
Encroach Param= -1, 0, 0, 0
BEGIN DESCRIPTION:
Multiple Run
END DESCRIPTION:

--- Elm 11.f01 (steady flow) ---

Flow Title=Multiple
Number of Profiles=7
Profile Names=10-year,25-year,50-year,1pct_min,100-year,1pct_plu,500-year
River Rch & RM= Elm 11,Reach-1,14189
     231     318     388     294     471     648     700
River Rch & RM= Elm 11,Reach-1,13895
     428     612     768     596     955    1310    1490
River Rch & RM= Elm 11,Reach-1,5691
     810    1190    1530    1210    1930    2660    3140
Boundary for River Rch & Prof#=Elm 11,Reach-1,1
Up Type=0
Dn Type=3
Dn Slope=0.005
Boundary for River Rch & Prof#=Elm 11,Reach-1,2
Up Type=0
Dn Type=3
Dn Slope=0.005
Boundary for River Rch & Prof#=Elm 11,Reach-1,3
Up Type=0
Dn Type=3
Dn Slope=0.005
Boundary for River Rch & Prof#=Elm 11,Reach-1,4
Up Type=0
Dn Type=3
Dn Slope=0.005
Boundary for River Rch & Prof#=Elm 11,Reach-1,5
Up Type=0
Dn Type=3
Dn Slope=0.005
Boundary for River Rch & Prof#=Elm 11,Reach-1,6
Up Type=0
Dn Type=3
Dn Slope=0.005
Boundary for River Rch & Prof#=Elm 11,Reach-1,7
Up Type=0
Dn Type=3
Dn Slope=0.005

--- Elm 11.g01 (geometry) ---

Geom Title=Existing Conditions

River Reach=Elm 11,Reach-1
Reach XY= 30
      1467305.00      6777488.00      1467847.68      6777982.30
      1467662.47      6778084.38      1467798.83      6778230.14
      1468070.21      6778337.49      1468599.33      6778339.98
      1469048.38      6778778.59      1469441.08      6778738.68
      1469796.81      6778891.66      1470285.41      6779267.80
      1470395.18      6779527.53      1470557.45      6779543.47
      1470899.81      6779793.44      1471006.46      6780034.48
      1471834.94      6779687.79      1472218.56      6779851.49
      1472325.18      6780037.96      1473043.17      6779936.34
      1473101.35      6779845.73      1473355.00      6779888.00
      1473565.50      6780136.80      1473968.57      6780100.98
      1474155.29      6780515.16      1474156.98      6781682.33
      1474699.54      6782185.55      1474708.22      6782680.01
      1475622.05      6783104.49      1475899.53      6783385.55
      1476012.82      6783894.19      1476255.00      6784088.00

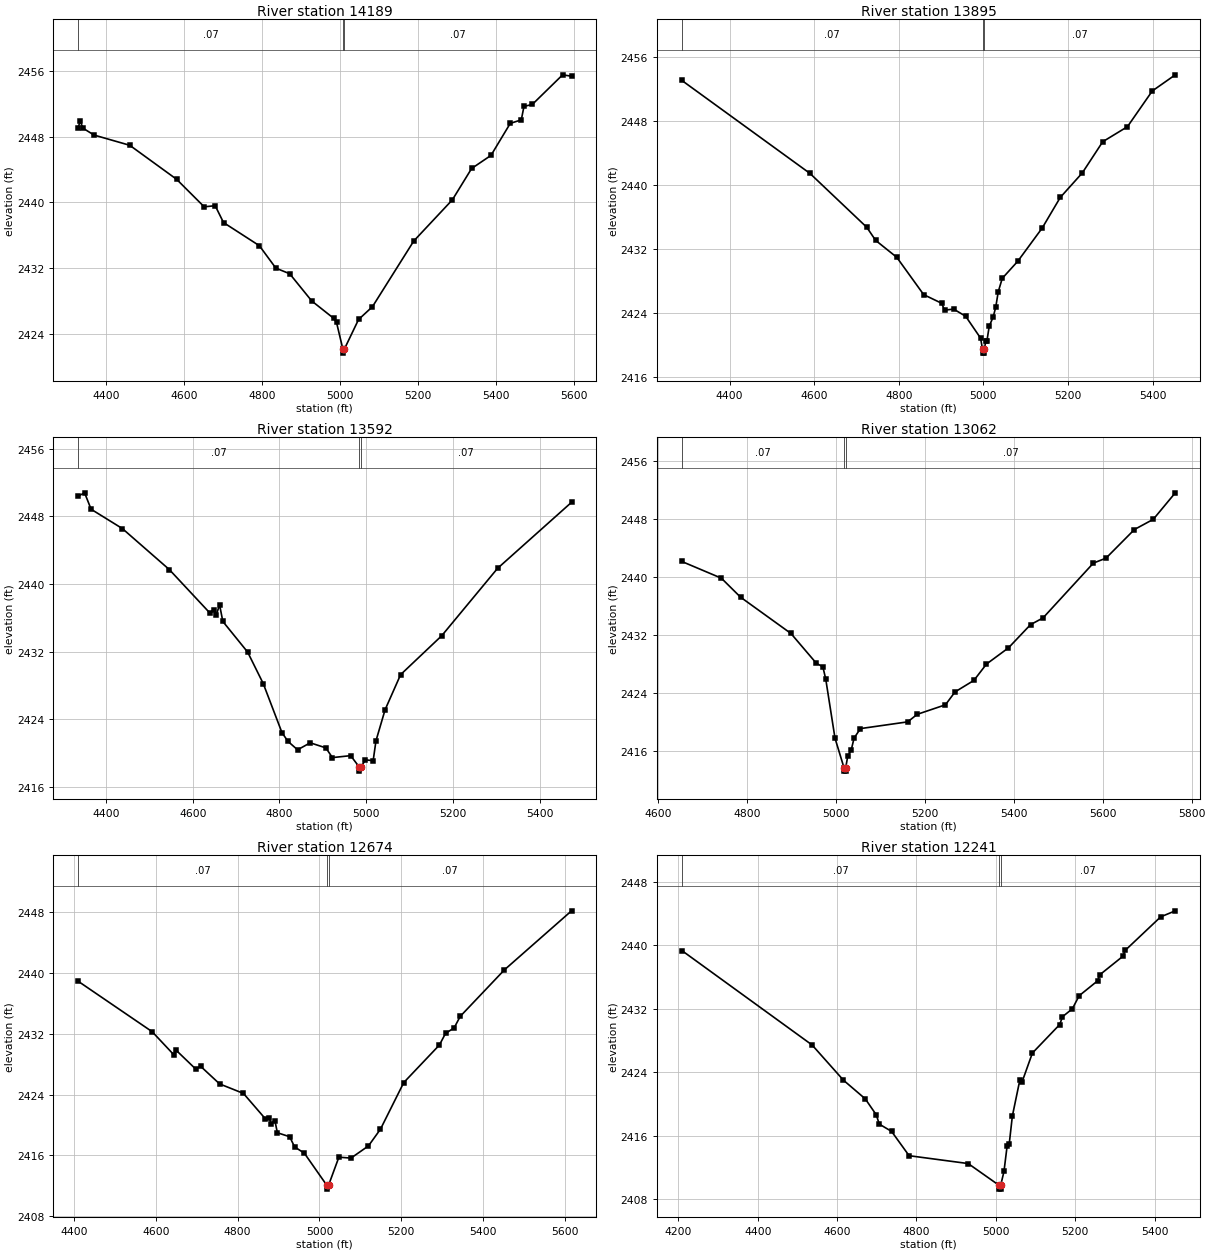
Type RM Length L Ch R = 1,14189,294,294,294
BEGIN DESCRIPTION:
elmc254
END DESCRIPTION:
XS GIS Cut Line= 3
      1466878.31      6778008.76      1467355.75      6777521.11
      1467759.13      6777099.85
#Sta/Elev= 30
  4328.5 2449.03  4333.7 2449.95  4340.9 2449.05  4369.2 2448.21  4461.0 2446.96
  4581.3 2442.81  4651.9 2439.46  4680.2 2439.59  4701.5 2437.54  4793.4 2434.72
  4835.8 2431.98  4871.2 2431.30  4927.8 2427.98  4984.4 2425.85  4991.4 2425.36
  5007.6 2422.12  5007.9 2421.62  5011.6 2422.12  5047.9 2425.72  5083.5 2427.28
  5189.5 2435.29  5288.5 2440.31  5337.9 2444.13  5387.6 2445.73  5437.0 2449.63
  5465.3 2450.06  5472.2 2451.70  5493.6 2451.94  5571.3 2455.55  5594.2 2455.38
#Mann=3,-1,0
  4328.5    0.07       0  5007.6    0.07       0  5011.6    0.07       0
Bank Sta=5007.6,5011.6
Exp/Cntr=0.3,0.1

Type RM Length L Ch R = 1,13895,303,303,303
BEGIN DESCRIPTION:
elmc64
END DESCRIPTION:
XS GIS Cut Line= 3
      1467095.36      6778235.95      1467577.87      6777702.38
      1467813.04      6777321.75
#Sta/Elev= 30
  4287.0 2453.06  4589.8 2441.43  4724.3 2434.68  4745.3 2433.04  4795.3 2430.92
  4858.9 2426.25  4901.4 2425.17  4908.2 2424.31  4929.8 2424.44  4958.2 2423.54
  4993.4 2420.81  4998.0 2419.43  4998.3 2418.93  5001.9 2418.93  5002.1 2419.43
  5006.0 2420.46  5008.4 2420.46  5013.9 2422.30  5023.3 2423.47  5029.3 2424.69
  5035.2 2426.61  5044.7 2428.29  5081.4 2430.43  5139.3 2434.60  5181.8 2438.41
  5233.9 2441.48  5282.3 2445.39  5340.7 2447.27  5399.4 2451.74  5453.8 2453.76
#Mann=3,-1,0
  4287.0    0.07       0  4998.0    0.07       0  5002.1    0.07       0
Bank Sta=4998,5002.1
Exp/Cntr=0.3,0.1

Type RM Length L Ch R = 1,13592,530,530,530
BEGIN DESCRIPTION:
elmc63
END DESCRIPTION:
XS GIS Cut Line= 3
      1467233.08      6778288.35      1467786.83      6777921.20
      1468056.59      6777531.94
#Sta/Elev= 30
  4335.6 2450.40  4350.6 2450.79  4365.6 2448.85  4437.8 2446.56  4546.1 2441.71
  4639.3 2436.59  4648.4 2436.99  4654.4 2436.38  4661.9 2437.55  4669.4 2435.58
  4726.6 2431.96  4762.7 2428.22  4805.8 2422.43  4819.8 2421.39  4841.8 2420.40
  4870.9 2421.23  4907.0 2420.63  4922.1 2419.48  4964.2 2419.71  4983.8 2418.38
  4984.0 2417.88  4987.9 2418.38  4998.4 2419.21  5016.1 2419.12  5022.6 2421.47
  5043.6 2425.14  5079.4 2429.29  5174.2 2433.89  5303.0 2441.86  5473.6 2449.67
#Mann=3,-1,0
  4335.6    0.07       0  4983.8    0.07       0  4987.9    0.07       0
Bank Sta=4983.8,4987.9
Exp/Cntr=0.3,0.1

Type RM Length L Ch R = 1,13062,388,388,388
BEGIN DESCRIPTION:
elmc62
END DESCRIPTION:
XS GIS Cut Line= 3
      1467520.10      6778438.50      1467847.14      6778168.19
      1468319.52      6777672.52
#Sta/Elev= 30
  4654.2 2442.16  4743.1 2439.85  4786.1 2437.23  4899.4 2432.21  4956.8 2428.07
  4971.1 2427.61  4977.6 2425.92  4998.4 2417.75  5018.5 2413.68  5018.8 2413.18
  5022.4 2413.18  5022.6 2413.68  5027.1 2415.25  5034.9 2416.10  5041.4 2417.76
  5055.7 2419.06  5161.8 2419.99  5183.2 2421.03  5246.7 2422.35  5268.2 2424.13
  5310.6 2425.72  5338.9 2427.98  5388.3 2430.22  5437.9 2433.43  5466.0 2434.36
  5579.2 2441.94  5607.5 2442.62  5671.4 2446.58  5713.8 2447.99  5763.2 2451.65
#Mann=3,-1,0
  4654.2    0.07       0  5018.5    0.07       0  5022.6    0.07       0
Bank Sta=5018.5,5022.6
Exp/Cntr=0.3,0.1

Type RM Length L Ch R = 1,12674,433,433,433
BEGIN DESCRIPTION:
elmc61
END DESCRIPTION:
XS GIS Cut Line= 3
      1467610.24      6778525.25      1468067.39      6778441.83
      1468480.57      6777825.39
#Sta/Elev= 30
  4409.7 2438.90  4590.9 2432.26  4644.2 2429.21  4649.2 2429.84  4697.4 2427.35
  4709.3 2427.72  4755.8 2425.40  4814.1 2424.15  4867.4 2420.83  4876.7 2420.97
  4882.1 2420.19  4891.0 2420.56  4897.1 2418.98  4927.1 2418.46  4939.2 2417.12
  4963.1 2416.29  5018.0 2412.07  5018.3 2411.57  5022.2 2412.07  5047.5 2415.77
  5077.1 2415.65  5119.8 2417.25  5149.2 2419.45  5206.2 2425.58  5293.3 2430.51
  5308.3 2432.04  5329.3 2432.76  5344.3 2434.28  5452.3 2440.39  5616.5 2448.15
#Mann=3,-1,0
  4409.7    0.07       0  5018.0    0.07       0  5022.2    0.07       0
Bank Sta=5018,5022.2
Exp/Cntr=0.3,0.1

Type RM Length L Ch R = 1,12241,447,447,447
BEGIN DESCRIPTION:
elmc60
END DESCRIPTION:
XS GIS Cut Line= 3
      1468204.22      6779039.15      1468570.26      6778337.49
      1468711.44      6777907.89
#Sta/Elev= 30
  4208.6 2439.35  4537.0 2427.45  4615.9 2423.02  4670.9 2420.67  4698.6 2418.66
  4706.2 2417.49  4737.2 2416.57  4781.4 2413.51  4930.3 2412.52  5007.6 2409.80
  5008.0 2409.30  5012.0 2409.30  5012.3 2409.80  5020.5 2411.53  5028.5 2414.77
  5033.7 2414.98  5041.6 2418.50  5060.3 2423.00  5065.6 2422.73  5092.1 2426.44
  5161.0 2430.03  5167.9 2431.01  5192.8 2432.01  5210.0 2433.66  5256.4 2435.53
  5262.6 2436.32  5320.0 2438.62  5325.8 2439.36  5415.4 2443.59  5452.2 2444.35
#Mann=3,-1,0
  4208.6    0.07       0  5007.6    0.07       0  5012.3    0.07       0
Bank Sta=5007.6,5012.3
Exp/Cntr=0.3,0.1

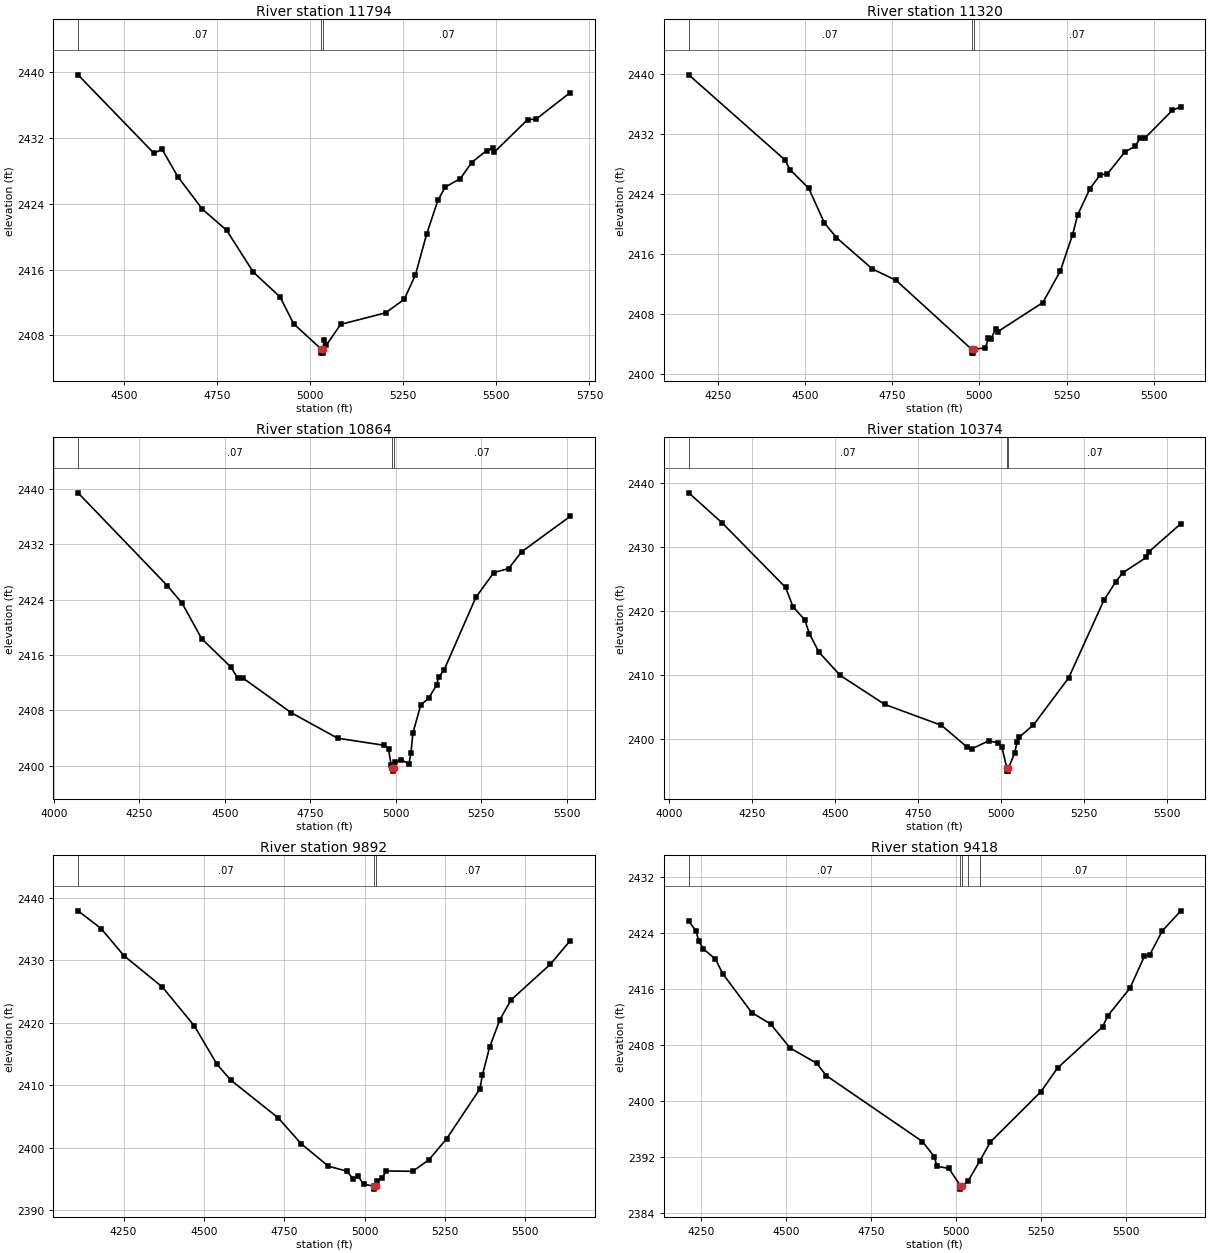
Type RM Length L Ch R = 1,11794,474,474,474
BEGIN DESCRIPTION:
elmc59
END DESCRIPTION:
XS GIS Cut Line= 3
      1468527.88      6779172.69      1468866.57      6778649.91
      1468928.35      6777954.65
#Sta/Elev= 30
  4377.1 2439.69  4581.3 2430.13  4602.4 2430.66  4644.8 2427.31  4711.2 2423.33
  4775.9 2420.79  4847.4 2415.70  4919.6 2412.66  4955.9 2409.40  5029.7 2406.33
  5030.0 2405.83  5034.0 2405.83  5034.4 2406.33  5037.9 2407.37  5043.0 2406.76
  5082.2 2409.33  5202.7 2410.73  5252.9 2412.38  5283.0 2415.37  5313.1 2420.34
  5343.3 2424.44  5363.3 2426.05  5403.5 2427.06  5433.6 2429.02  5473.8 2430.47
  5489.8 2430.79  5494.8 2430.29  5584.2 2434.25  5606.5 2434.29  5698.0 2437.52
#Mann=3,-1,0
  4377.1    0.07       0  5029.7    0.07       0  5034.4    0.07       0
Bank Sta=5029.7,5034.4
Exp/Cntr=0.3,0.1

Type RM Length L Ch R = 1,11320,456,456,456
BEGIN DESCRIPTION:
elmc58
END DESCRIPTION:
XS GIS Cut Line= 3
      1468881.62      6779469.67      1469280.62      6778738.67
      1469629.14      6778278.31
#Sta/Elev= 30
  4167.2 2439.89  4442.5 2428.55  4457.8 2427.22  4510.9 2424.76  4555.6 2420.16
  4590.6 2418.16  4693.2 2413.99  4761.5 2412.46  4978.2 2403.25  4978.6 2402.75
  4982.9 2402.75  4983.3 2403.25  5017.6 2403.46  5025.9 2404.80  5032.2 2404.60
  5046.7 2405.92  5053.0 2405.62  5182.0 2409.50  5231.9 2413.69  5267.3 2418.57
  5281.8 2421.20  5317.2 2424.72  5346.3 2426.54  5367.1 2426.67  5417.1 2429.60
  5446.2 2430.35  5460.8 2431.41  5475.3 2431.49  5552.7 2435.13  5577.4 2435.64
#Mann=3,-1,0
  4167.2    0.07       0  4978.2    0.07       0  4983.3    0.07       0
Bank Sta=4978.2,4983.3
Exp/Cntr=0.3,0.1

Type RM Length L Ch R = 1,10864,490,490,490
BEGIN DESCRIPTION:
elmc57
END DESCRIPTION:
XS GIS Cut Line= 3
      1469095.22      6779586.43      1469688.29      6778871.50
      1469939.50      6778428.46
#Sta/Elev= 30
  4071.1 2439.43  4332.3 2426.00  4375.3 2423.48  4432.6 2418.34  4517.2 2414.28
  4538.1 2412.64  4552.4 2412.68  4694.3 2407.64  4829.8 2403.96  4965.2 2402.94
  4978.6 2402.41  4986.0 2400.14  4990.0 2399.70  4990.4 2399.20  4995.1 2399.70
  4999.0 2400.49  5015.5 2400.84  5038.4 2400.25  5044.1 2401.82  5050.0 2404.73
  5073.0 2408.78  5096.0 2409.74  5119.0 2411.64  5124.9 2412.75  5140.8 2413.80
  5233.9 2424.32  5286.5 2427.91  5329.8 2428.48  5367.3 2430.89  5509.3 2436.02
#Mann=3,-1,0
  4071.1    0.07       0  4990.0    0.07       0  4995.1    0.07       0
Bank Sta=4990,4995.1
Exp/Cntr=0.3,0.1

Type RM Length L Ch R = 1,10374,482,482,482
BEGIN DESCRIPTION:
elmc56
END DESCRIPTION:
XS GIS Cut Line= 3
      1469468.95      6779863.44      1470065.58      6779136.80
      1470443.37      6778748.86
#Sta/Elev= 30
  4059.8 2438.48  4159.9 2433.80  4351.5 2423.69  4373.8 2420.66  4408.9 2418.65
  4423.3 2416.43  4452.0 2413.56  4515.8 2409.94  4650.0 2405.40  4820.8 2402.13
  4899.0 2398.68  4913.4 2398.48  4962.9 2399.71  4991.6 2399.38  5002.7 2398.78
  5017.4 2395.47  5017.8 2394.97  5022.2 2394.97  5022.6 2395.47  5041.1 2397.78
  5048.3 2399.48  5055.2 2400.29  5097.7 2402.18  5203.9 2409.56  5309.9 2421.69
  5345.3 2424.54  5366.4 2425.97  5437.2 2428.37  5444.3 2429.21  5541.5 2433.65
#Mann=3,-1,0
  4059.8    0.07       0  5017.4    0.07       0  5022.6    0.07       0
Bank Sta=5017.4,5022.6
Exp/Cntr=0.3,0.1

Type RM Length L Ch R = 1,9892,474,474,474
BEGIN DESCRIPTION:
elmc55
END DESCRIPTION:
XS GIS Cut Line= 3
      1469682.53      6780076.99      1470324.59      6779458.21
      1470603.39      6778882.68
#Sta/Elev= 30
  4108.3 2437.92  4180.2 2435.08  4250.7 2430.76  4371.1 2425.70  4470.1 2419.50
  4540.8 2413.33  4583.3 2410.83  4731.7 2404.74  4802.5 2400.63  4887.4 2397.02
  4944.0 2396.24  4965.1 2394.98  4979.2 2395.50  4996.8 2394.12  5029.0 2393.85
  5029.4 2393.35  5034.3 2393.85  5037.2 2394.70  5054.3 2395.08  5066.9 2396.26
  5150.1 2396.20  5200.9 2398.08  5255.8 2401.45  5358.9 2409.41  5366.9 2411.68
  5389.1 2416.08  5421.1 2420.50  5455.8 2423.65  5578.0 2429.36  5639.5 2433.11
#Mann=3,-1,0
  4108.3    0.07       0  5029.0    0.07       0  5034.3    0.07       0
Bank Sta=5029,5034.3
Exp/Cntr=0.3,0.1

Type RM Length L Ch R = 1,9418,487,487,487
BEGIN DESCRIPTION:
elmc54
END DESCRIPTION:
XS GIS Cut Line= 3
      1470139.73      6780223.81      1470711.05      6779685.47
      1471047.37      6779115.96
#Sta/Elev= 30
  4215.0 2425.72  4236.8 2424.30  4244.1 2422.91  4258.3 2421.73  4293.5 2420.30
  4314.9 2418.21  4399.9 2412.65  4456.1 2410.99  4512.7 2407.58  4590.8 2405.40
  4619.2 2403.62  4902.0 2394.19  4937.1 2392.01  4944.4 2390.65  4979.6 2390.34
  5013.4 2387.88  5013.8 2387.38  5018.7 2387.88  5035.5 2388.50  5070.2 2391.38
  5101.8 2394.13  5250.2 2401.32  5299.0 2404.71  5431.6 2410.61  5447.2 2412.21
  5511.6 2416.11  5554.5 2420.71  5570.1 2420.92  5607.2 2424.34  5661.4 2427.20
#Mann=5,-1,0
  4215.0    0.07       0  5013.4    0.07       0  5018.7    0.07       0
  5035.5    0.16       0  5070.2    0.07       0
Bank Sta=5013.4,5018.7
Exp/Cntr=0.3,0.1

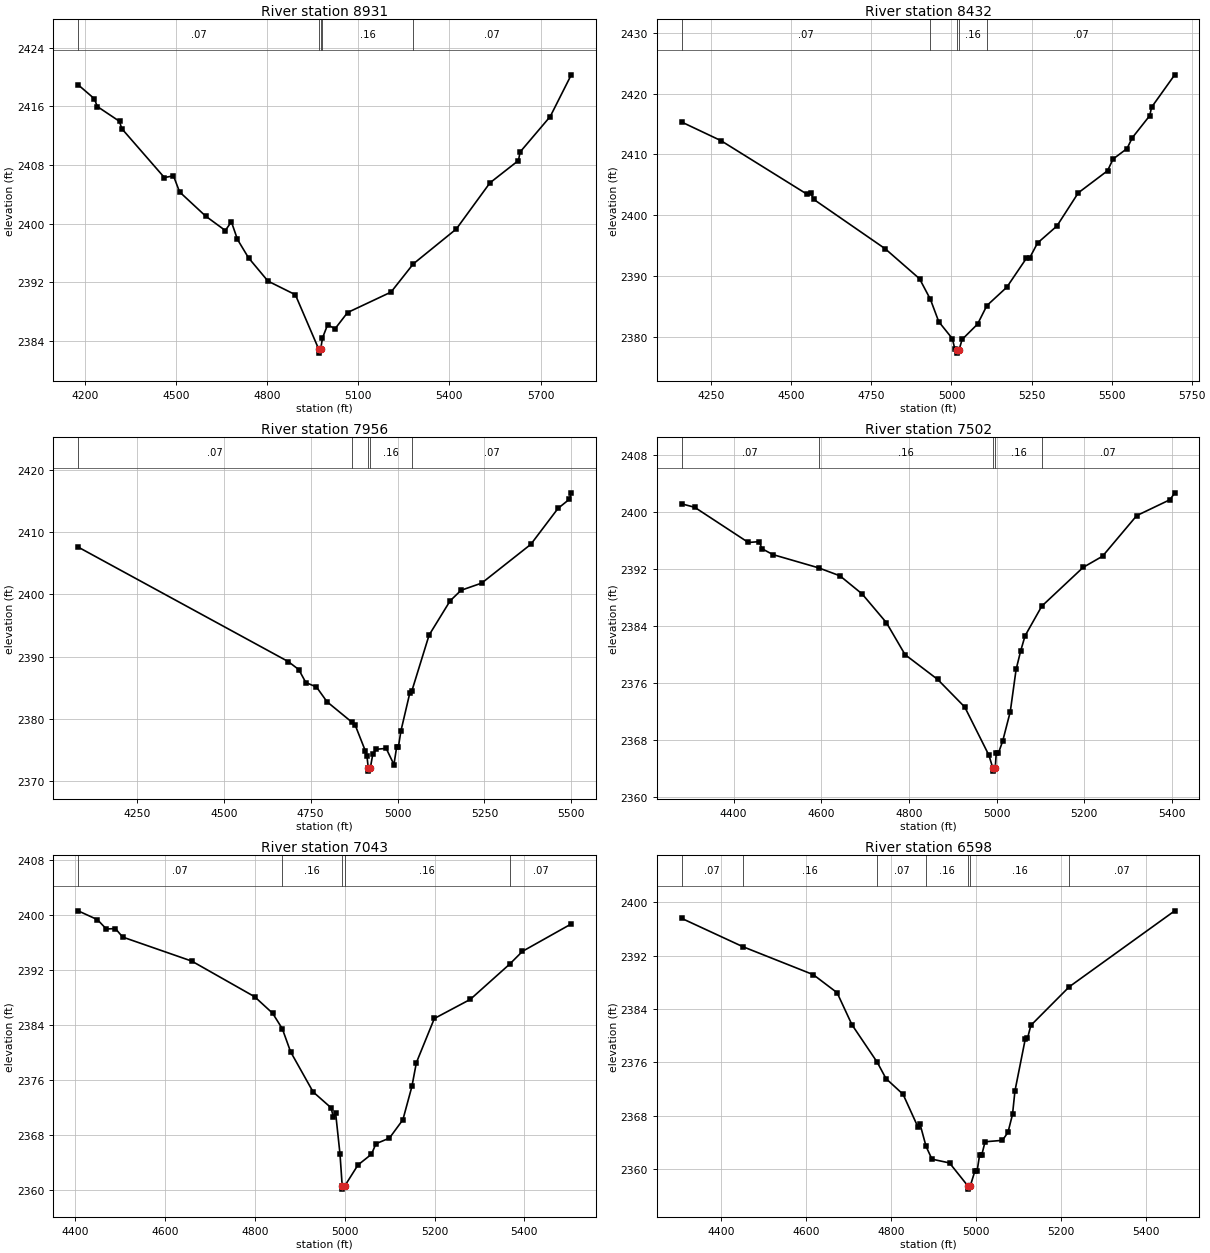
Type RM Length L Ch R = 1,8931,499,499,499
BEGIN DESCRIPTION:
elmc53
END DESCRIPTION:
XS GIS Cut Line= 3
      1470930.60      6780841.17      1470988.20      6780021.59
      1471154.99      6779238.04
#Sta/Elev= 30
  4178.4 2418.94  4231.7 2417.04  4241.7 2415.97  4314.7 2413.95  4321.9 2412.97
  4462.3 2406.29  4492.3 2406.52  4512.4 2404.33  4597.7 2401.05  4662.8 2399.07
  4682.8 2400.26  4702.9 2397.85  4739.2 2395.35  4803.1 2392.18  4893.3 2390.32
  4970.6 2382.86  4971.1 2382.36  4976.4 2382.86  4982.6 2384.43  4999.3 2386.21
  5024.1 2385.69  5065.0 2387.89  5208.1 2390.68  5281.3 2394.52  5422.9 2399.28
  5533.6 2405.57  5627.3 2408.61  5632.7 2409.77  5731.9 2414.61  5801.1 2420.29
#Mann=5,-1,0
  4178.4    0.07       0  4970.6    0.07       0  4976.4    0.07       0
  4982.6    0.16       0  5281.3    0.07       0
Bank Sta=4970.6,4976.4
Exp/Cntr=0.3,0.1

Type RM Length L Ch R = 1,8432,476,476,476
BEGIN DESCRIPTION:
elmc52
END DESCRIPTION:
XS GIS Cut Line= 3
      1471404.46      6780731.08      1471425.14      6779888.33
      1471307.99      6779201.14
#Sta/Elev= 30
  4157.0 2415.33  4280.1 2412.26  4550.2 2403.40  4560.2 2403.64  4570.2 2402.58
  4792.9 2394.47  4900.3 2389.53  4934.2 2386.14  4960.3 2382.46  5002.7 2379.68
  5010.5 2377.97  5017.7 2377.79  5018.2 2377.29  5023.5 2377.79  5033.2 2379.54
  5081.5 2382.07  5110.5 2385.11  5172.8 2388.14  5233.7 2392.88  5243.8 2392.93
  5268.9 2395.42  5329.1 2398.20  5396.0 2403.67  5487.3 2407.30  5504.6 2409.23
  5548.1 2410.95  5564.7 2412.74  5619.1 2416.37  5624.9 2417.76  5697.1 2423.09
#Mann=5,-1,0
  4157.0    0.07       0  4934.2    0.16       0  5017.7    0.07       0
  5023.5    0.16       0  5110.5    0.07       0
Bank Sta=5017.7,5023.5
Exp/Cntr=0.3,0.1

Type RM Length L Ch R = 1,7956,454,454,454
BEGIN DESCRIPTION:
elmc51
END DESCRIPTION:
XS GIS Cut Line= 3
      1471681.43      6780594.28      1471834.94      6779687.79
      1471905.00      6779192.82
#Sta/Elev= 30
  4080.6 2407.62  4685.4 2389.22  4715.8 2387.93  4736.1 2385.84  4766.5 2385.15
  4796.9 2382.77  4868.5 2379.49  4878.1 2379.01  4907.0 2374.91  4912.0 2373.99
  4915.7 2372.12  4916.2 2371.62  4921.6 2372.12  4928.8 2374.36  4938.9 2375.13
  4967.3 2375.27  4989.6 2372.67  4997.4 2375.50  5002.4 2375.50  5009.9 2378.13
  5035.6 2384.25  5041.4 2384.55  5090.7 2393.47  5151.3 2398.98  5182.7 2400.67
  5242.2 2401.83  5383.6 2408.06  5461.8 2413.83  5494.7 2415.31  5499.9 2416.33
#Mann=5,-1,0
  4080.6    0.07       0  4868.5    0.16       0  4915.7    0.07       0
  4921.6    0.16       0  5041.4    0.07       0
Bank Sta=4915.7,4921.6
Exp/Cntr=0.3,0.1

Type RM Length L Ch R = 1,7502,459,459,459
BEGIN DESCRIPTION:
elmc50
END DESCRIPTION:
XS GIS Cut Line= 3
      1471958.42      6780517.48      1472203.57      6779841.89
      1472282.11      6779442.94
#Sta/Elev= 30
  4281.3 2401.11  4311.3 2400.62  4433.8 2395.68  4459.1 2395.80  4464.4 2394.82
  4489.7 2393.98  4594.0 2392.12  4642.7 2391.00  4693.3 2388.46  4748.8 2384.42
  4791.4 2379.93  4865.8 2376.45  4927.6 2372.57  4982.9 2365.78  4991.2 2364.08
  4991.7 2363.58  4997.2 2364.08  4999.4 2366.13  5004.5 2366.13  5014.2 2367.82
  5031.4 2371.93  5044.7 2377.85  5054.9 2380.40  5065.1 2382.57  5103.3 2386.74
  5197.6 2392.18  5241.9 2393.75  5319.9 2399.45  5396.0 2401.69  5406.6 2402.65
#Mann=5,-1,0
  4281.3    0.07       0  4594.0    0.16       0  4991.2    0.07       0
  4997.2    0.16       0  5103.3    0.07       0
Bank Sta=4991.2,4997.2
Exp/Cntr=0.3,0.1

Type RM Length L Ch R = 1,7043,445,445,445
BEGIN DESCRIPTION:
elmc49
END DESCRIPTION:
XS GIS Cut Line= 3
      1472515.71      6780630.97      1472541.08      6780037.32
      1472552.42      6779533.04
#Sta/Elev= 30
  4405.8 2400.62  4448.8 2399.34  4468.8 2397.97  4488.9 2398.04  4505.1 2396.80
  4659.0 2393.30  4799.1 2388.11  4839.2 2385.70  4860.8 2383.44  4879.2 2380.09
  4929.3 2374.25  4969.3 2371.94  4974.5 2370.57  4979.5 2371.17  4989.3 2365.16
  4994.1 2360.59  4994.6 2360.09  5000.2 2360.59  5029.3 2363.61  5059.3 2365.17
  5069.3 2366.70  5099.3 2367.52  5129.3 2370.19  5149.4 2375.04  5159.4 2378.51
  5199.4 2384.94  5279.4 2387.72  5367.4 2392.87  5395.7 2394.72  5504.4 2398.71
#Mann=5,-1,0
  4405.8    0.07       0  4860.8    0.16       0  4994.1    0.07       0
  5000.2    0.16       0  5367.4    0.07       0
Bank Sta=4994.1,5000.2
Exp/Cntr=0.3,0.1

Type RM Length L Ch R = 1,6598,422,422,422
BEGIN DESCRIPTION:
elmc48
END DESCRIPTION:
XS GIS Cut Line= 3
      1472775.99      6780607.64      1472954.34      6779937.78
      1472779.66      6779503.82
#Sta/Elev= 30
  4306.8 2397.62  4451.4 2393.35  4616.9 2389.16  4673.0 2386.45  4708.0 2381.64
  4767.6 2376.00  4788.2 2373.55  4828.3 2371.20  4863.3 2366.29  4868.5 2366.67
  4882.5 2363.37  4896.3 2361.46  4937.7 2360.89  4980.6 2357.46  4981.1 2356.96
  4986.7 2357.46  4997.3 2359.66  5002.6 2359.66  5008.4 2362.06  5013.8 2362.14
  5021.3 2364.07  5062.1 2364.28  5075.2 2365.47  5086.0 2368.18  5091.7 2371.70
  5115.8 2379.43  5121.2 2379.58  5129.1 2381.54  5219.6 2387.34  5467.8 2398.74
#Mann=7,-1,0
  4306.8    0.07       0  4451.4    0.16       0  4767.6    0.07       0
  4882.5    0.16       0  4980.6    0.07       0  4986.7    0.16       0
  5219.6    0.07       0
Bank Sta=4980.6,4986.7
Exp/Cntr=0.3,0.1

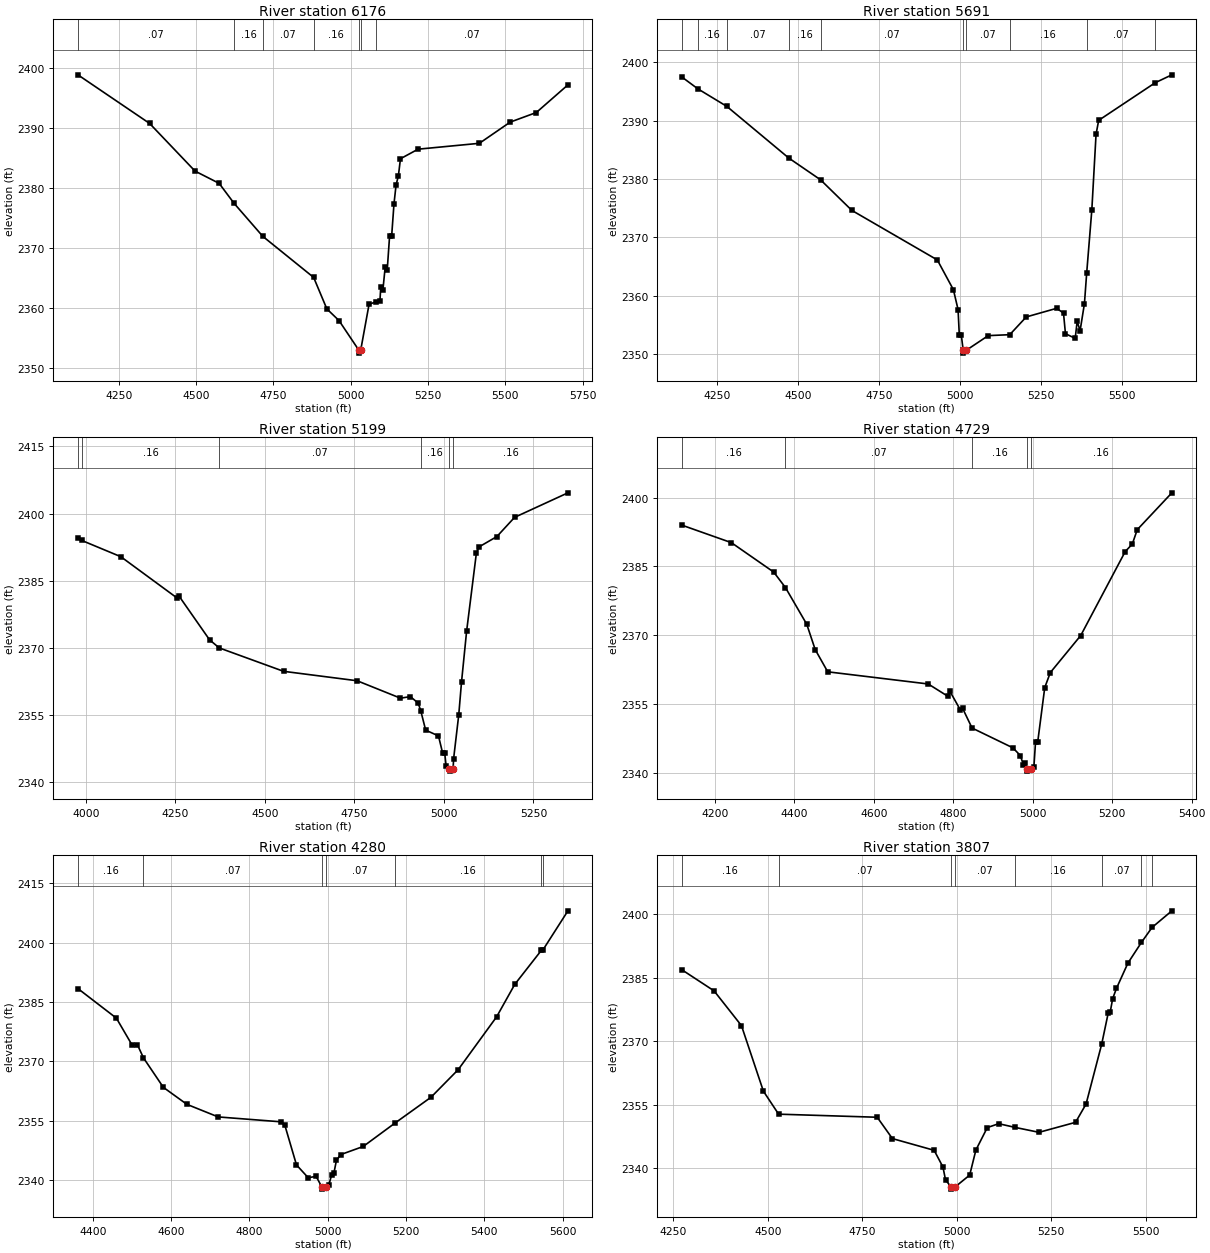
Type RM Length L Ch R = 1,6176,485,485,485
BEGIN DESCRIPTION:
elmc47
END DESCRIPTION:
XS GIS Cut Line= 4
      1472906.13      6780717.74      1473295.20      6779926.64
      1473273.22      6779836.73      1472816.06      6779432.95
#Sta/Elev= 30
  4118.4 2398.80  4350.2 2390.70  4497.0 2382.76  4574.9 2380.72  4623.2 2377.39
  4716.0 2371.89  4880.5 2365.04  4923.1 2359.80  4962.5 2357.85  5026.4 2352.93
  5026.9 2352.43  5032.6 2352.93  5059.6 2360.57  5081.8 2360.97  5094.7 2361.10
  5097.5 2363.51  5104.2 2362.89  5111.7 2366.77  5118.4 2366.35  5126.0 2371.98
  5132.6 2371.92  5140.2 2377.33  5146.9 2380.44  5154.4 2381.98  5161.1 2384.82
  5218.0 2386.41  5416.2 2387.39  5515.8 2390.92  5600.3 2392.52  5702.5 2397.13
#Mann=7,-1,0
  4118.4    0.07       0  4623.2    0.16       0  4716.0    0.07       0
  4880.5    0.16       0  5026.4    0.07       0  5032.6    0.16       0
  5081.8    0.07       0
Bank Sta=5026.4,5032.6
Exp/Cntr=0.3,0.1

Type RM Length L Ch R = 1,5691,492,492,492
BEGIN DESCRIPTION:
elmc46
END DESCRIPTION:
XS GIS Cut Line= 3
      1473042.96      6780804.49      1473584.85      6780138.36
      1474130.43      6779780.28
#Sta/Elev= 30
  4141.3 2397.50  4190.4 2395.48  4280.1 2392.46  4471.1 2383.61  4569.1 2379.88
  4665.6 2374.64  4929.2 2366.15  4978.8 2361.05  4993.2 2357.65  4997.0 2353.31
  5003.1 2353.31  5009.0 2350.68  5009.5 2350.18  5018.8 2350.68  5086.3 2353.18
  5152.6 2353.34  5203.5 2356.38  5297.3 2357.86  5318.4 2357.04  5324.4 2353.51
  5354.5 2352.71  5360.5 2355.62  5369.6 2354.03  5383.0 2358.68  5389.8 2363.84
  5405.8 2374.76  5418.8 2387.69  5426.9 2390.07  5601.4 2396.52  5652.6 2397.87
#Mann=10,-1,0
  4141.3    0.07       0  4190.4    0.16       0  4280.1    0.07       0
  4471.1    0.16       0  4569.1    0.07       0  5009.0    0.07       0
  5018.8    0.07       0  5152.6    0.16       0  5389.8    0.07       0
  5601.4    0.16       0
Bank Sta=5009,5018.8
Exp/Cntr=0.3,0.1

Type RM Length L Ch R = 1,5199,470,470,470
BEGIN DESCRIPTION:
elmc45
END DESCRIPTION:
XS GIS Cut Line= 3
      1473223.20      6780834.49      1474006.73      6780178.15
      1474270.52      6779953.94
#Sta/Elev= 30
  3977.9 2394.46  3988.3 2394.00  4097.7 2390.36  4254.1 2381.17  4260.6 2381.52
  4345.5 2371.79  4372.5 2369.98  4552.1 2364.75  4757.6 2362.64  4878.6 2358.75
  4906.4 2359.10  4928.1 2357.63  4935.5 2355.85  4948.9 2351.61  4984.7 2350.32
  4996.2 2346.51  5002.1 2346.51  5006.1 2343.53  5015.4 2342.95  5015.9 2342.45
  5025.5 2342.95  5027.0 2345.25  5041.3 2355.01  5049.0 2362.32  5063.3 2373.74
  5090.7 2391.27  5098.4 2392.57  5147.8 2394.86  5197.2 2399.15  5346.2 2404.63
#Mann=6,-1,0
  3977.9    0.07       0  3988.3    0.16       0  4372.5    0.07       0
  4935.5    0.16       0  5015.4    0.07       0  5025.5    0.16       0
Bank Sta=5015.4,5025.5
Exp/Cntr=0.3,0.1

Type RM Length L Ch R = 1,4729,449,449,449
BEGIN DESCRIPTION:
elmc44
END DESCRIPTION:
XS GIS Cut Line= 3
      1473316.62      6780874.55      1474154.53      6780596.33
      1474474.55      6780454.10
#Sta/Elev= 30
  4117.1 2394.01  4241.8 2390.19  4348.3 2383.78  4377.8 2380.41  4431.5 2372.40
  4452.6 2366.91  4484.2 2362.05  4737.1 2359.40  4786.5 2356.72  4791.7 2357.80
  4818.1 2353.72  4823.4 2354.13  4847.4 2349.80  4950.1 2345.49  4968.9 2343.81
  4976.5 2341.81  4981.8 2342.25  4984.9 2340.91  4985.4 2340.41  4995.1 2340.91
  5003.0 2341.37  5007.1 2346.70  5012.6 2346.75  5030.3 2358.60  5044.3 2361.88
  5120.9 2369.96  5232.8 2388.25  5250.6 2389.88  5263.1 2393.02  5350.2 2401.05
#Mann=5,-1,0
  4117.1    0.16       0  4377.8    0.07       0  4847.4    0.16       0
  4984.9    0.07       0  4995.1    0.16       0
Bank Sta=4984.9,4995.1
Exp/Cntr=0.3,0.1

Type RM Length L Ch R = 1,4280,473,473,473
BEGIN DESCRIPTION:
elmc43
END DESCRIPTION:
XS GIS Cut Line= 3
      1473466.77      6781008.04      1474104.73      6781028.98
      1474664.77      6780777.79
#Sta/Elev= 30
  4361.7 2388.41  4460.0 2380.94  4500.0 2374.17  4513.9 2374.19  4529.2 2370.91
  4580.0 2363.47  4640.1 2359.18  4720.1 2356.00  4880.2 2354.77  4890.2 2353.98
  4920.2 2343.88  4950.2 2340.64  4970.3 2341.00  4985.2 2338.27  4985.7 2337.77
  4995.4 2338.27  5002.9 2338.84  5010.2 2341.43  5015.7 2341.79  5022.2 2345.00
  5033.2 2346.49  5090.7 2348.54  5170.8 2354.37  5263.9 2360.97  5333.4 2367.94
  5431.6 2381.28  5478.0 2389.48  5545.9 2398.06  5550.4 2398.24  5613.8 2408.04
#Mann=7,-1,0
  4361.7    0.16       0  4529.2    0.07       0  4985.2    0.07       0
  4995.4    0.07       0  5170.8    0.16       0  5545.9    0.07       0
  5550.4    0.16       0
Bank Sta=4985.2,4995.4
Exp/Cntr=0.3,0.1

Type RM Length L Ch R = 1,3807,470,470,470
BEGIN DESCRIPTION:
elmc42
END DESCRIPTION:
XS GIS Cut Line= 3
      1473430.07      6781418.50      1474154.48      6781486.56
      1474720.77      6781425.26
#Sta/Elev= 30
  4272.4 2386.91  4357.7 2381.92  4430.2 2373.71  4488.3 2358.22  4528.6 2352.79
  4789.6 2352.06  4829.8 2347.02  4940.3 2344.25  4963.6 2340.31  4970.4 2337.27
  4985.3 2335.58  4985.8 2335.08  4995.6 2335.58  5034.4 2338.40  5050.8 2344.31
  5081.0 2349.62  5111.2 2350.54  5153.2 2349.69  5217.9 2348.50  5314.6 2350.86
  5342.5 2355.19  5383.8 2369.32  5401.3 2376.77  5406.3 2376.87  5412.9 2380.09
  5423.0 2382.52  5453.2 2388.47  5488.9 2393.35  5517.2 2396.91  5569.6 2400.83
#Mann=8,-1,0
  4272.4    0.16       0  4528.6    0.07       0  4985.3    0.07       0
  4995.6    0.07       0  5153.2    0.16       0  5383.8    0.07       0
  5488.9    0.16       0  5517.2    0.07       0
Bank Sta=4985.3,4995.6
Exp/Cntr=0.3,0.1

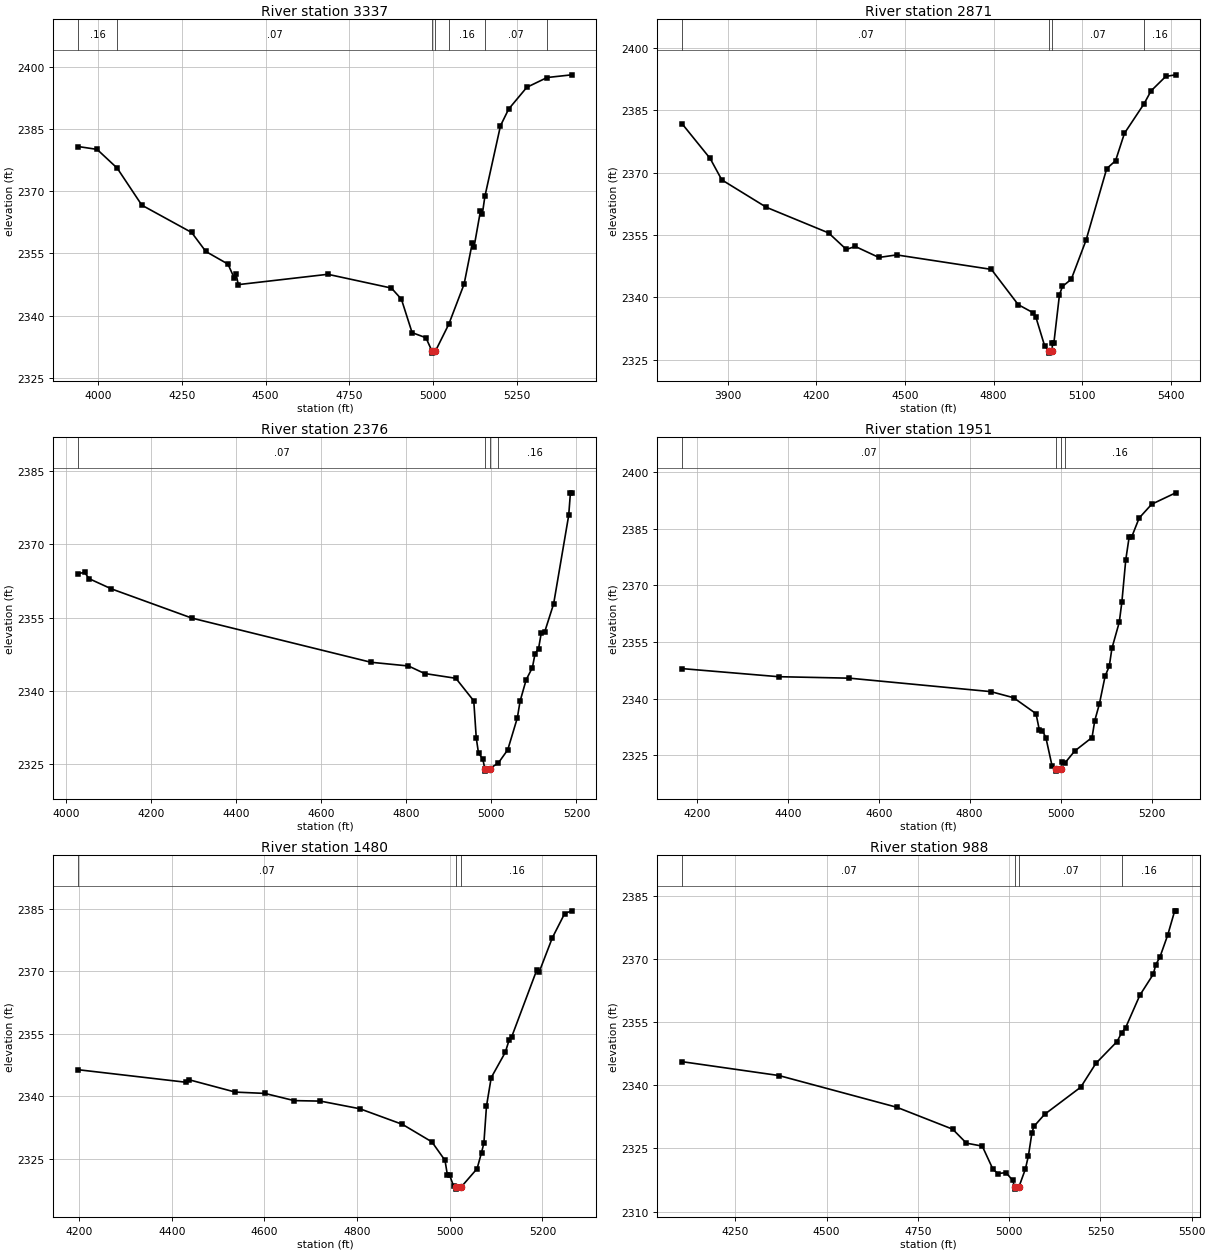
Type RM Length L Ch R = 1,3337,466,466,466
BEGIN DESCRIPTION:
elmc41
END DESCRIPTION:
XS GIS Cut Line= 3
      1473359.95      6781675.45      1474224.29      6781879.02
      1474768.27      6781665.43
#Sta/Elev= 30
  3940.8 2380.78  3997.4 2380.09  4057.4 2375.57  4130.9 2366.64  4279.5 2360.05
  4321.8 2355.47  4387.8 2352.43  4406.6 2349.05  4411.7 2350.13  4418.6 2347.48
  4685.7 2349.97  4875.3 2346.65  4905.1 2343.97  4937.0 2335.90  4978.3 2334.67
  4996.2 2331.46  4996.7 2330.96  5006.7 2331.46  5046.5 2337.94  5092.1 2347.60
  5116.6 2357.55  5121.9 2356.60  5141.0 2365.29  5146.4 2364.44  5154.1 2368.75
  5200.6 2385.78  5225.0 2389.81  5279.2 2395.06  5339.7 2397.42  5413.2 2398.07
#Mann=7,-1,0
  3940.8    0.16       0  4057.4    0.07       0  4996.2    0.07       0
  5006.7    0.07       0  5046.5    0.16       0  5154.1    0.07       0
  5339.7    0.16       0
Bank Sta=4996.2,5006.7
Exp/Cntr=0.3,0.1

Type RM Length L Ch R = 1,2871,495,495,495
BEGIN DESCRIPTION:
elmc40
END DESCRIPTION:
XS GIS Cut Line= 3
      1473430.05      6782252.77      1474682.14      6782164.47
      1475098.61      6782169.34
#Sta/Elev= 30
  3744.8 2381.77  3840.0 2373.41  3879.4 2368.27  4030.7 2361.66  4241.0 2355.51
  4301.1 2351.54  4331.2 2352.26  4411.4 2349.61  4471.5 2350.22  4792.3 2346.74
  4883.2 2338.26  4932.7 2336.35  4942.7 2335.33  4972.8 2328.32  4987.5 2327.10
  4988.0 2326.60  4998.2 2327.10  4998.9 2329.02  5003.9 2329.02  5022.9 2340.63
  5032.9 2342.63  5062.9 2344.37  5112.9 2353.76  5182.9 2370.97  5212.9 2372.88
  5242.9 2379.46  5309.4 2386.57  5332.9 2389.66  5382.9 2393.15  5416.5 2393.53
#Mann=4,-1,0
  3744.8    0.07       0  4987.5    0.07       0  4998.2    0.07       0
  5309.4    0.16       0
Bank Sta=4987.5,4998.2
Exp/Cntr=0.3,0.1

Type RM Length L Ch R = 1,2376,425,425,425
BEGIN DESCRIPTION:
elmc39
END DESCRIPTION:
XS GIS Cut Line= 3
      1473780.46      6782953.56      1474704.35      6782652.21
      1474854.96      6782538.03
#Sta/Elev= 30
  4028.2 2363.98  4043.5 2364.24  4054.0 2362.95  4106.6 2360.86  4295.9 2354.88
  4716.7 2345.85  4805.0 2345.09  4842.9 2343.55  4916.5 2342.57  4958.6 2337.95
  4964.5 2330.33  4969.8 2327.23  4979.6 2326.13  4984.6 2324.08  4985.1 2323.58
  4995.8 2324.08  5016.5 2325.26  5038.5 2327.94  5061.1 2334.48  5067.4 2337.85
  5081.9 2342.29  5096.5 2344.76  5102.7 2347.61  5111.0 2348.66  5117.3 2351.84
  5125.6 2352.12  5146.4 2357.80  5181.8 2375.88  5185.9 2380.51  5189.0 2380.51
#Mann=4,-1,0
  4028.2    0.07       0  4984.6    0.07       0  4995.8    0.07       0
  5016.5    0.16       0
Bank Sta=4984.6,4995.8
Exp/Cntr=0.3,0.1

Type RM Length L Ch R = 1,1951,471,471,471
BEGIN DESCRIPTION:
elmc38
END DESCRIPTION:
XS GIS Cut Line= 3
      1474497.95      6783460.77      1475057.20      6782844.08
      1475177.82      6782621.46
#Sta/Elev= 30
  4167.5 2347.96  4379.7 2345.82  4535.7 2345.43  4846.7 2341.87  4896.7 2340.26
  4946.0 2336.04  4953.5 2331.61  4960.2 2331.49  4967.7 2329.70  4981.2 2322.28
  4989.0 2321.35  4989.5 2320.85  5000.2 2321.35  5003.6 2323.25  5009.3 2322.96
  5031.1 2326.17  5069.2 2329.74  5075.2 2334.20  5085.3 2338.58  5097.9 2345.93
  5107.2 2348.64  5112.9 2353.29  5129.1 2360.23  5134.8 2365.54  5143.4 2376.74
  5151.0 2382.88  5156.6 2382.83  5172.8 2387.77  5200.4 2391.43  5253.2 2394.44
#Mann=4,-1,0
  4167.5    0.07       0  4989.0    0.07       0  5000.2    0.07       0
  5009.3    0.16       0
Bank Sta=4989,5000.2
Exp/Cntr=0.3,0.1

Type RM Length L Ch R = 1,1480,492,492,492
BEGIN DESCRIPTION:
elmc37
END DESCRIPTION:
XS GIS Cut Line= 3
      1474878.36      6783580.92      1475457.54      6783026.17
      1475502.38      6782766.72
#Sta/Elev= 30
  4198.0 2346.38  4431.0 2343.37  4438.2 2343.95  4537.3 2341.01  4600.8 2340.70
  4664.3 2338.97  4721.0 2338.85  4805.9 2337.02  4898.0 2333.27  4961.5 2329.07
  4989.8 2324.64  4995.1 2321.02  5000.0 2321.02  5008.3 2318.44  5013.3 2318.24
  5013.8 2317.74  5024.6 2318.24  5059.0 2322.64  5068.6 2326.51  5073.7 2328.79
  5079.3 2337.64  5089.5 2344.48  5119.9 2350.56  5128.4 2353.61  5133.5 2354.21
  5188.2 2370.41  5193.3 2369.89  5221.4 2378.02  5248.0 2383.83  5263.3 2384.49
#Mann=3,-1,0
  4198.0    0.07       0  5013.3    0.07       0  5024.6    0.16       0
Bank Sta=5013.3,5024.6
Exp/Cntr=0.3,0.1

Type RM Length L Ch R = 1,988,471,471,471
BEGIN DESCRIPTION:
elmc36
END DESCRIPTION:
XS GIS Cut Line= 3
      1475041.88      6783744.44      1475823.40      6783306.63
      1476004.99      6782888.02
#Sta/Elev= 30
  4104.2 2345.62  4369.4 2342.33  4692.4 2334.79  4845.4 2329.58  4883.1 2326.26
  4926.5 2325.56  4956.0 2320.02  4969.8 2319.05  4991.5 2319.26  5009.4 2317.47
  5015.5 2315.84  5016.0 2315.34  5026.8 2315.84  5044.6 2320.11  5053.0 2323.30
  5062.6 2328.78  5068.1 2330.25  5097.0 2333.09  5196.3 2339.57  5237.8 2345.23
  5295.6 2350.39  5308.6 2352.53  5319.1 2353.69  5358.2 2361.42  5394.9 2366.40
  5401.8 2368.69  5412.7 2370.38  5434.5 2375.72  5453.6 2381.46  5456.3 2381.46
#Mann=4,-1,0
  4104.2    0.07       0  5015.5    0.07       0  5026.8    0.07       0
  5308.6    0.16       0
Bank Sta=5015.5,5026.8
Exp/Cntr=0.3,0.1

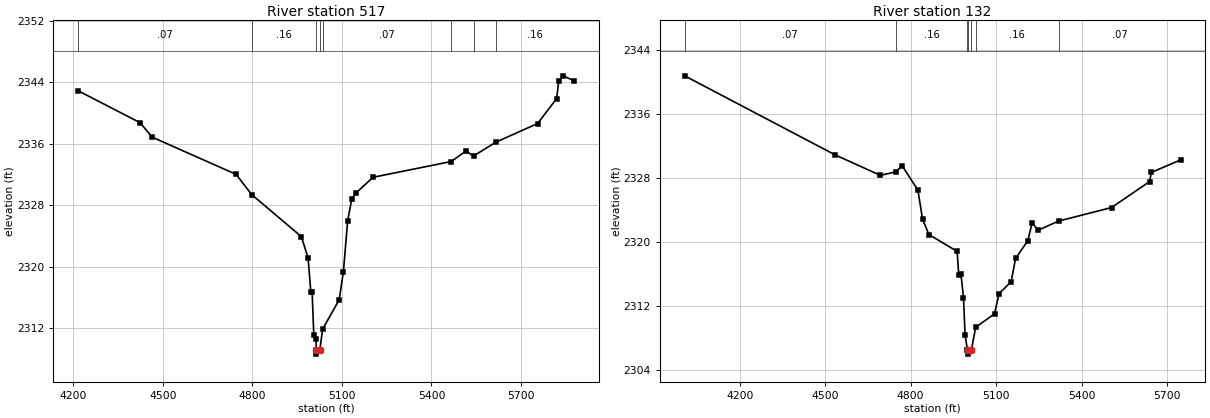
Type RM Length L Ch R = 1,517,385,385,385
BEGIN DESCRIPTION:
elmc35
END DESCRIPTION:
XS GIS Cut Line= 3
      1475178.74      6783811.18      1475958.47      6783729.53
      1476553.57      6783083.70
#Sta/Elev= 30
  4216.0 2342.89  4423.4 2338.74  4463.6 2336.86  4745.1 2332.01  4797.7 2329.37
  4964.0 2323.90  4986.5 2321.11  4995.7 2316.65  5000.0 2316.65  5005.6 2311.14
  5012.9 2310.63  5014.1 2309.10  5014.6 2308.60  5025.4 2309.10  5035.4 2311.87
  5090.6 2315.67  5104.8 2319.32  5119.0 2325.94  5133.2 2328.86  5147.3 2329.59
  5204.1 2331.63  5466.3 2333.68  5515.4 2335.05  5541.0 2334.41  5617.3 2336.23
  5755.8 2338.63  5819.3 2341.87  5826.7 2344.14  5840.9 2344.84  5878.2 2344.20
#Mann=8,-1,0
  4216.0    0.07       0  4797.7    0.16       0  5014.1    0.07       0
  5025.4    0.16       0  5035.4    0.07       0  5466.3    0.16       0
  5541.0    0.07       0  5617.3    0.16       0
Bank Sta=5014.1,5025.4
Exp/Cntr=0.3,0.1

Type RM Length L Ch R = 1,132,0,0,0
BEGIN DESCRIPTION:
elmc253
END DESCRIPTION:
XS GIS Cut Line= 5
      1475191.99      6783904.61      1476009.63      6784098.17
      1476209.85      6783994.72      1476326.65      6783801.17
      1476489.65      6783382.02
#Sta/Elev= 30
  4006.5 2340.81  4533.7 2330.93  4693.5 2328.35  4747.9 2328.78  4770.0 2329.55
  4825.4 2326.50  4841.8 2322.85  4864.0 2320.94  4963.3 2318.82  4968.9 2315.82
  4976.6 2315.99  4985.5 2313.03  4991.1 2308.32  4999.5 2306.46  5001.9 2306.46
  5002.4 2305.96  5013.3 2306.46  5028.2 2309.32  5094.6 2311.01  5110.1 2313.52
  5152.8 2315.03  5168.4 2317.95  5211.1 2320.14  5226.6 2322.39  5247.9 2321.48
  5319.3 2322.62  5505.7 2324.32  5639.0 2327.57  5644.9 2328.71  5747.9 2330.28
#Mann=7,-1,0
  4006.5    0.07       0  4747.9    0.16       0  4999.5    0.07       0
  5001.9    0.07       0  5013.3    0.07       0  5028.2    0.16       0
  5319.3    0.07       0
Bank Sta=5001.9,5013.3
Exp/Cntr=0.3,0.1

Chan Stop Cuts=-1