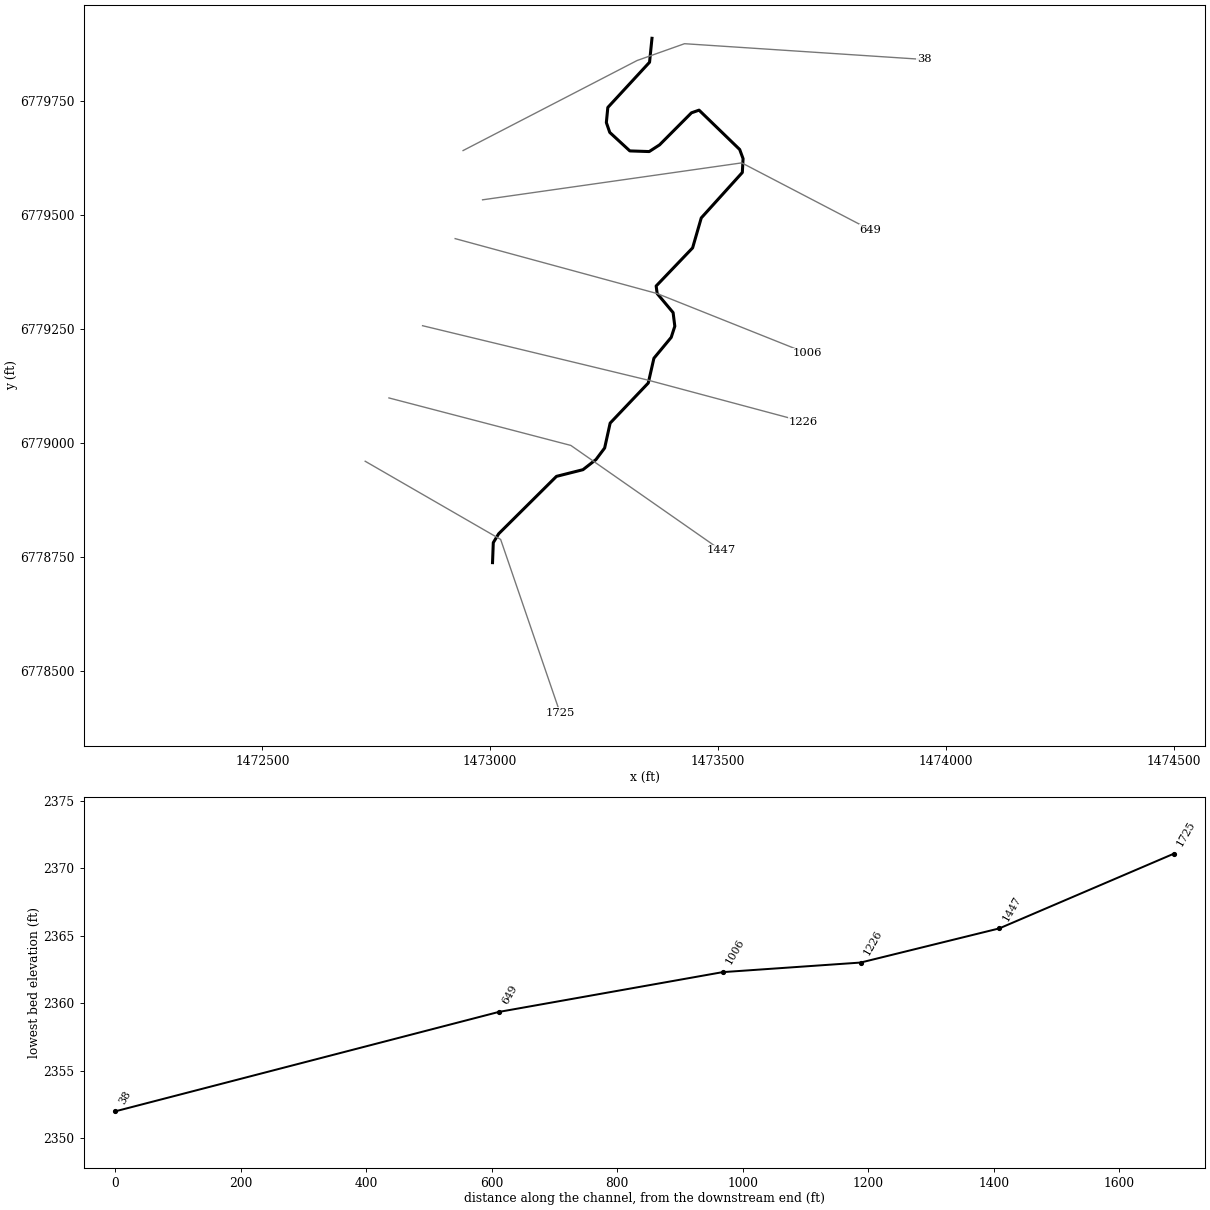
--- Elm 12.prj (project) ---

Proj Title=Elm 12 Base Level Engineering
Current Plan=p01
Default Exp/Contr=0.3,0.1
English Units
Geom File=g01
Flow File=f01
Plan File=p01
BEGIN DESCRIPTION:
Elm 12
END DESCRIPTION:

--- Elm 12.p01 (plan) ---

Plan Title=Multiple Run
Short Identifier=Multiple
Geom File=g01
Flow File=f01
Subcritical Flow
K Sum by GR= 0
Std Step Tol= 0.01
Critical Tol= 0.01
Num of Std Step Trials= 20
Max Error Tol= 0.3
Flow Tol Ratio= 0.001
Split Flow NTrial= 30
Split Flow Tol= 0.02
Split Flow Ratio= 0.02
Log Output Level= 0
Friction Slope Method= 1
Unsteady Friction Slope Method= 2
Unsteady Bridges Friction Slope Method= 1
Parabolic Critical Depth
Global Vel Dist=  1 , 1 , 1
Global Log Level= 0
CheckData=True
Encroach Param= -1, 0, 0, 0
BEGIN DESCRIPTION:
Multiple Run
END DESCRIPTION:

--- Elm 12.f01 (steady flow) ---

Flow Title=Multiple
Number of Profiles=7
Profile Names=10-year,25-year,50-year,1pct_min,100-year,1pct_plu,500-year
River Rch & RM= Elm 12,Reach-1,1725
     221     306     375     286     458     631     691
River Rch & RM= Elm 12,Reach-1,1447
     411     588     739     575     922    1270    1450
Boundary for River Rch & Prof#=Elm 12,Reach-1,1
Up Type=0
Dn Type=3
Dn Slope=0.005
Boundary for River Rch & Prof#=Elm 12,Reach-1,2
Up Type=0
Dn Type=3
Dn Slope=0.005
Boundary for River Rch & Prof#=Elm 12,Reach-1,3
Up Type=0
Dn Type=3
Dn Slope=0.005
Boundary for River Rch & Prof#=Elm 12,Reach-1,4
Up Type=0
Dn Type=3
Dn Slope=0.005
Boundary for River Rch & Prof#=Elm 12,Reach-1,5
Up Type=0
Dn Type=3
Dn Slope=0.005
Boundary for River Rch & Prof#=Elm 12,Reach-1,6
Up Type=0
Dn Type=3
Dn Slope=0.005
Boundary for River Rch & Prof#=Elm 12,Reach-1,7
Up Type=0
Dn Type=3
Dn Slope=0.005

--- Elm 12.g01 (geometry) ---

Geom Title=Existing Conditions

River Reach=Elm 12,Reach-1
Reach XY= 30
      1473005.00      6778738.00      1473006.68      6778781.86
      1473018.47      6778801.28      1473145.34      6778927.21
      1473203.57      6778941.89      1473232.14      6778964.16
      1473251.11      6778989.43      1473263.18      6779044.02
      1473346.85      6779131.95      1473359.25      6779186.27
      1473397.21      6779232.07      1473405.12      6779256.46
      1473401.39      6779286.37      1473366.39      6779328.13
      1473364.17      6779344.72      1473444.17      6779428.32
      1473463.18      6779494.04      1473553.30      6779593.65
      1473554.96      6779623.95      1473547.54      6779644.09
      1473458.35      6779730.41      1473441.68      6779724.56
      1473371.66      6779654.28      1473348.91      6779639.58
      1473306.37      6779641.01      1473262.34      6779681.57
      1473254.84      6779703.20      1473258.08      6779736.32
      1473349.67      6779835.49      1473355.00      6779888.00

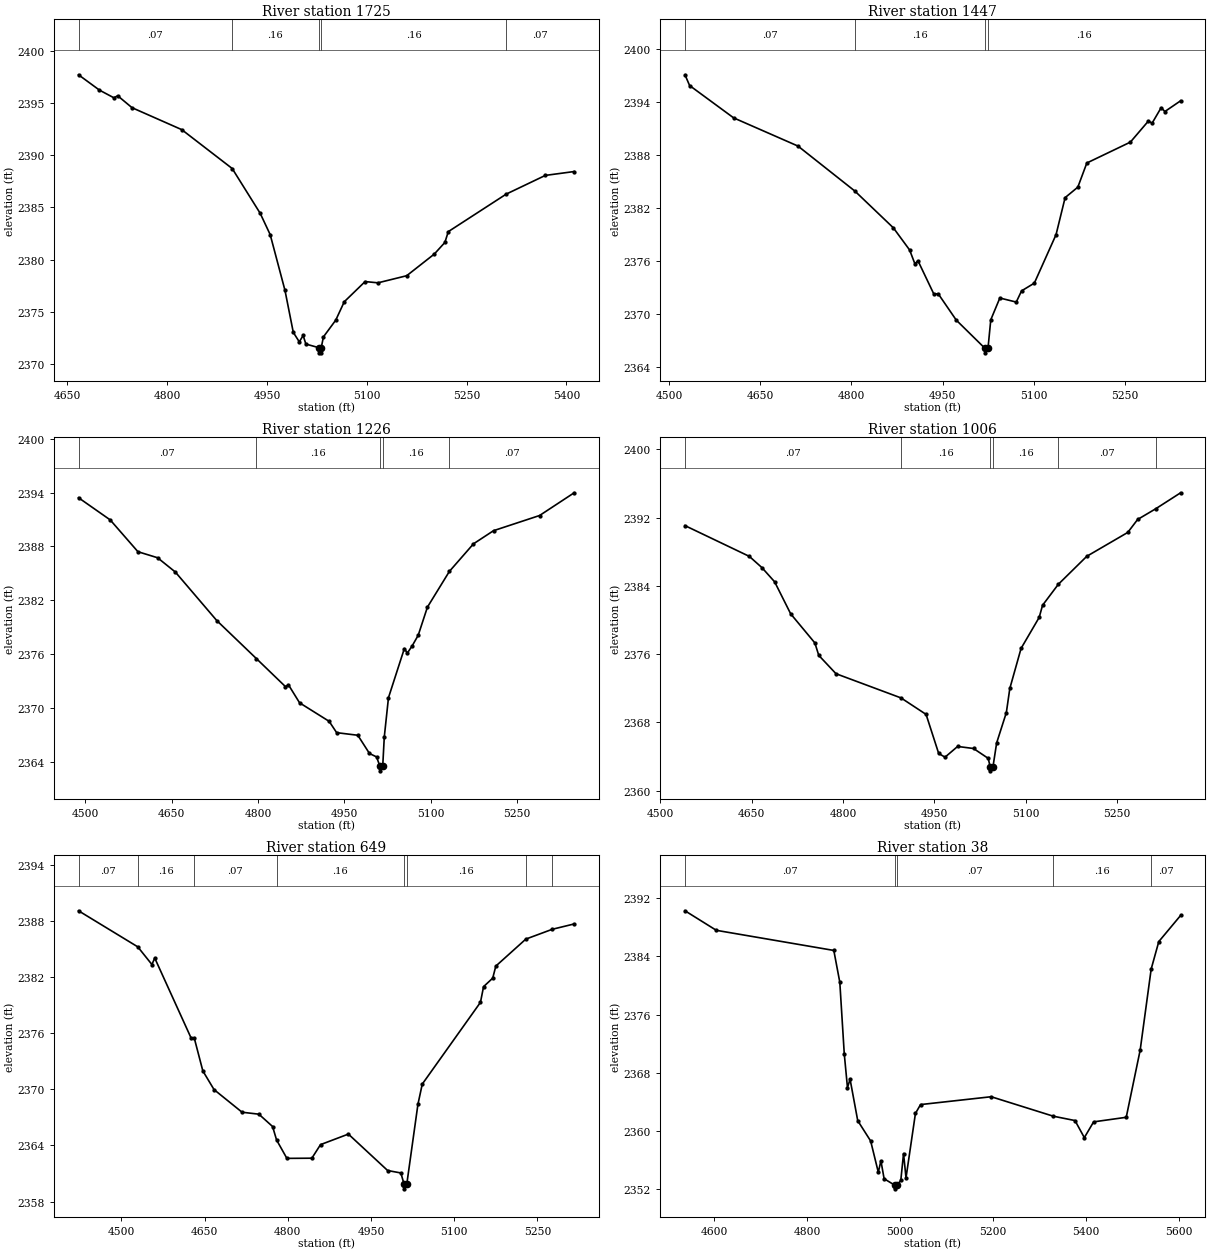
Type RM Length L Ch R = 1,1725,278,278,278
BEGIN DESCRIPTION:
elmc257
END DESCRIPTION:
XS GIS Cut Line= 3
      1472725.48      6778960.37      1473022.82      6778788.91
      1473153.02      6778409.15
#Sta/Elev= 30
  4666.9 2397.69  4698.4 2396.22  4720.0 2395.49  4725.8 2395.68  4747.3 2394.54
  4822.0 2392.44  4897.8 2388.72  4939.8 2384.44  4954.9 2382.39  4977.1 2377.06
  4989.6 2373.04  4998.6 2372.13  5004.4 2372.74  5008.5 2371.92  5027.6 2371.58
  5027.9 2371.08  5031.4 2371.08  5031.6 2371.58  5034.9 2372.61  5053.4 2374.21
  5066.2 2375.97  5097.5 2377.90  5116.8 2377.78  5160.0 2378.46  5201.4 2380.53
  5217.3 2381.64  5222.5 2382.68  5309.5 2386.27  5368.3 2388.06  5411.6 2388.43
#Mann=5,-1,0
  4666.9    0.07       0  4897.8    0.16       0  5027.6    0.07       0
  5031.6    0.16       0  5309.5    0.07       0
Bank Sta=5027.6,5031.6
Exp/Cntr=0.3,0.1

Type RM Length L Ch R = 1,1447,221,221,221
BEGIN DESCRIPTION:
elmc134
END DESCRIPTION:
XS GIS Cut Line= 3
      1472777.62      6779099.23      1473176.90      6778995.07
      1473506.77      6778765.03
#Sta/Elev= 30
  4526.3 2397.10  4533.9 2395.88  4606.3 2392.21  4712.1 2389.01  4805.5 2383.91
  4868.9 2379.73  4895.6 2377.22  4904.2 2375.66  4909.3 2376.00  4935.4 2372.22
  4942.6 2372.25  4972.3 2369.26  5019.6 2366.05  5019.9 2365.55  5024.4 2366.05
  5029.0 2369.30  5043.9 2371.77  5070.9 2371.31  5079.6 2372.58  5100.6 2373.46
  5136.3 2378.96  5151.2 2383.16  5172.1 2384.35  5186.9 2387.09  5258.5 2389.46
  5288.1 2391.85  5294.2 2391.61  5309.1 2393.37  5315.2 2392.93  5341.1 2394.15
#Mann=4,-1,0
  4526.3    0.07       0  4805.5    0.16       0  5019.6    0.07       0
  5024.4    0.16       0
Bank Sta=5019.6,5024.4
Exp/Cntr=0.3,0.1

Type RM Length L Ch R = 1,1226,220,220,220
BEGIN DESCRIPTION:
elmc256
END DESCRIPTION:
XS GIS Cut Line= 3
      1472851.42      6779257.65      1473346.17      6779138.30
      1473686.85      6779047.17
#Sta/Elev= 30
  4488.0 2393.42  4543.1 2390.95  4591.3 2387.41  4625.4 2386.74  4656.3 2385.15
  4728.3 2379.75  4797.1 2375.52  4847.8 2372.39  4852.9 2372.60  4872.3 2370.59
  4923.7 2368.53  4936.7 2367.27  4973.5 2366.98  4993.8 2364.95  5006.1 2364.57
  5012.0 2363.52  5012.3 2363.02  5016.8 2363.52  5019.5 2366.77  5026.8 2371.16
  5054.4 2376.63  5059.6 2376.12  5068.2 2376.95  5078.5 2378.11  5094.5 2381.24
  5132.7 2385.22  5174.6 2388.29  5209.4 2389.75  5289.5 2391.44  5349.6 2393.97
#Mann=5,-1,0
  4488.0    0.07       0  4797.1    0.16       0  5012.0    0.07       0
  5016.8    0.16       0  5132.7    0.07       0
Bank Sta=5012,5016.8
Exp/Cntr=0.3,0.1

Type RM Length L Ch R = 1,1006,357,357,357
BEGIN DESCRIPTION:
elmc133
END DESCRIPTION:
XS GIS Cut Line= 3
      1472922.98      6779448.64      1473366.39      6779328.13
      1473695.59      6779196.88
#Sta/Elev= 30
  4540.5 2391.07  4646.2 2387.46  4666.9 2386.14  4687.7 2384.48  4714.1 2380.72
  4753.8 2377.31  4760.2 2375.85  4788.5 2373.70  4895.3 2370.86  4936.4 2368.93
  4957.1 2364.35  4967.5 2363.91  4988.2 2365.17  5014.3 2364.93  5038.5 2363.77
  5041.5 2362.81  5041.9 2362.31  5046.3 2362.81  5052.3 2365.59  5068.2 2369.14
  5073.9 2371.97  5092.4 2376.67  5122.1 2380.30  5127.7 2381.73  5153.6 2384.19
  5200.3 2387.47  5267.6 2390.27  5283.8 2391.79  5313.4 2393.04  5354.4 2394.92
#Mann=6,-1,0
  4540.5    0.07       0  4895.3    0.16       0  5041.5    0.07       0
  5046.3    0.16       0  5153.6    0.07       0  5313.4    0.16       0
Bank Sta=5041.5,5046.3
Exp/Cntr=0.3,0.1

Type RM Length L Ch R = 1,649,611,611,611
BEGIN DESCRIPTION:
elmc132
END DESCRIPTION:
XS GIS Cut Line= 3
      1472983.14      6779533.75      1473552.00      6779614.78
      1473834.78      6779467.60
#Sta/Elev= 30
  4422.7 2389.12  4529.5 2385.26  4555.0 2383.37  4560.1 2384.06  4625.8 2375.48
  4631.2 2375.53  4646.8 2371.98  4667.0 2369.98  4717.5 2367.56  4747.8 2367.35
  4772.5 2366.03  4779.7 2364.59  4798.3 2362.62  4843.3 2362.64  4858.9 2364.09
  4909.1 2365.22  4979.9 2361.32  5003.7 2361.06  5009.5 2359.86  5009.9 2359.36
  5014.4 2359.86  5034.5 2368.41  5042.3 2370.57  5147.2 2379.32  5152.8 2381.00
  5169.3 2381.91  5174.9 2383.20  5229.0 2386.09  5276.7 2387.14  5316.1 2387.71
#Mann=8,-1,0
  4422.7    0.07       0  4529.5    0.16       0  4631.2    0.07       0
  4779.7    0.16       0  5009.5    0.07       0  5014.4    0.16       0
  5229.0    0.07       0  5276.7    0.16       0
Bank Sta=5009.5,5014.4
Exp/Cntr=0.3,0.1

Type RM Length L Ch R = 1,38,0,0,0
BEGIN DESCRIPTION:
elmc255
END DESCRIPTION:
XS GIS Cut Line= 4
      1472940.38      6779641.79      1473322.30      6779839.26
      1473426.46      6779876.15      1473951.87      6779841.56
#Sta/Elev= 30
  4536.9 2390.28  4604.4 2387.59  4857.3 2384.82  4870.2 2380.44  4879.8 2370.58
  4886.7 2365.93  4892.3 2367.09  4908.8 2361.38  4936.6 2358.59  4953.1 2354.28
  4958.7 2355.86  4965.6 2353.39  4988.5 2352.50  4988.8 2352.00  4993.4 2352.50
  5001.5 2353.16  5007.4 2356.86  5012.7 2353.51  5033.0 2362.38  5044.0 2363.60
  5196.1 2364.68  5329.8 2362.00  5376.5 2361.40  5396.6 2359.05  5416.6 2361.22
  5486.8 2361.85  5516.8 2371.10  5540.5 2382.26  5556.9 2386.04  5603.9 2389.64
#Mann=5,-1,0
  4536.9    0.07       0  4988.5    0.07       0  4993.4    0.07       0
  5329.8    0.16       0  5540.5    0.07       0
Bank Sta=4988.5,4993.4
Exp/Cntr=0.3,0.1

Chan Stop Cuts=-1