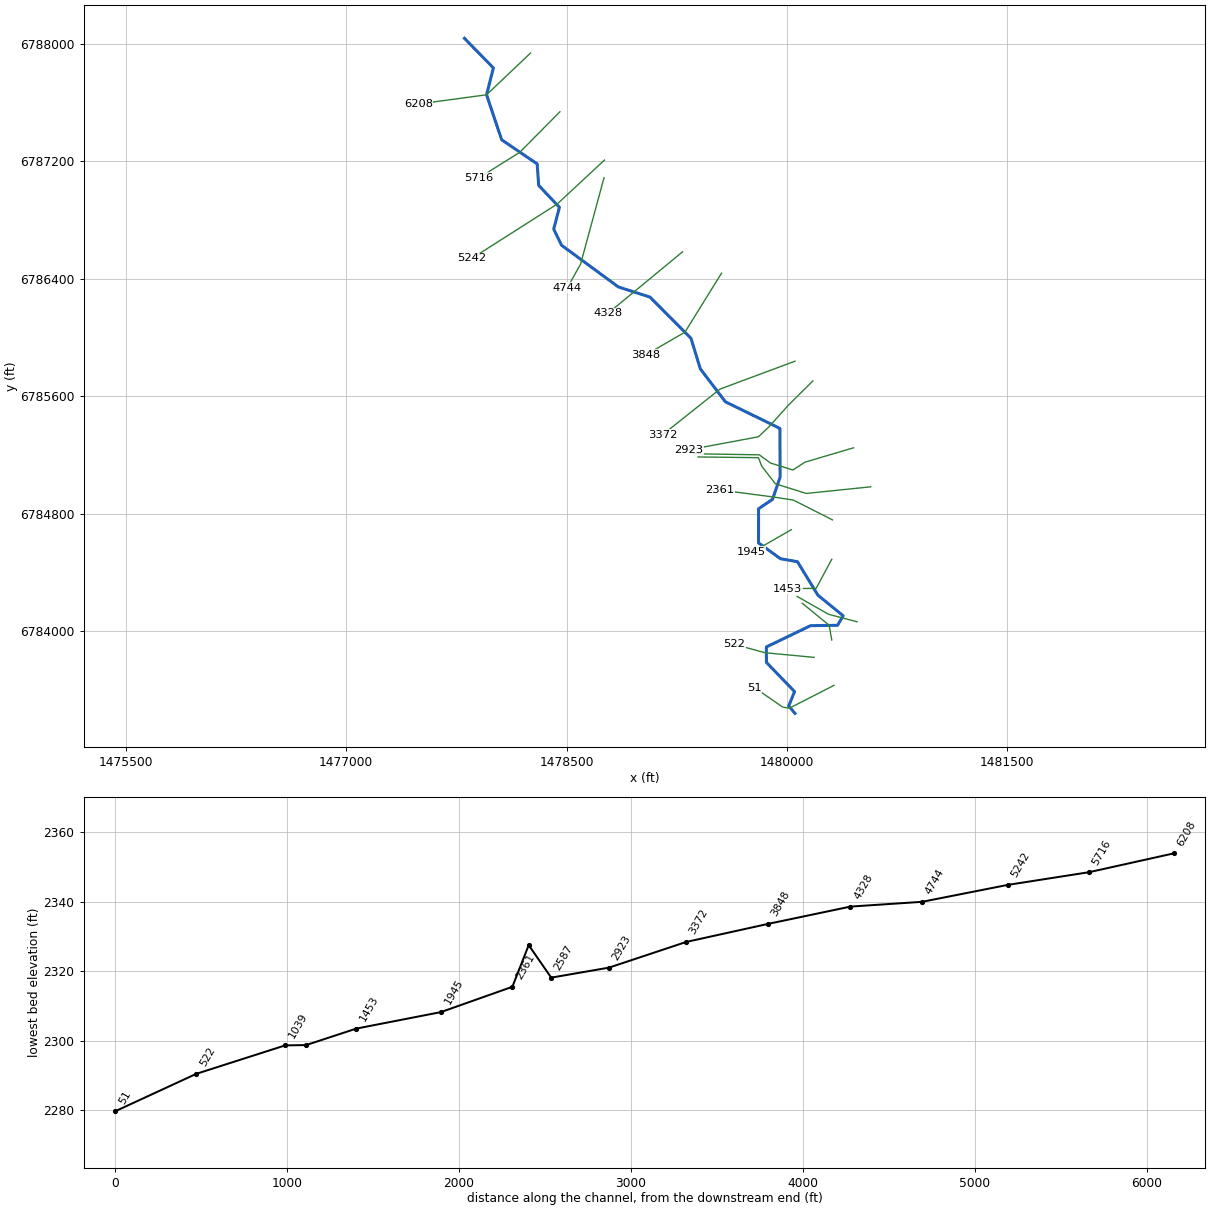
--- Elm 13.prj (project) ---

Proj Title=Elm 13 Base Level Engineering
Current Plan=p01
Default Exp/Contr=0.3,0.1
English Units
Geom File=g01
Flow File=f01
Plan File=p01
BEGIN DESCRIPTION:
Elm 13
END DESCRIPTION:

--- Elm 13.p01 (plan) ---

Plan Title=Multiple Run
Short Identifier=Multiple
Geom File=g01
Flow File=f01
Subcritical Flow
K Sum by GR= 0
Std Step Tol= 0.01
Critical Tol= 0.01
Num of Std Step Trials= 20
Max Error Tol= 0.3
Flow Tol Ratio= 0.001
Split Flow NTrial= 30
Split Flow Tol= 0.02
Split Flow Ratio= 0.02
Log Output Level= 0
Friction Slope Method= 1
Unsteady Friction Slope Method= 2
Unsteady Bridges Friction Slope Method= 1
Parabolic Critical Depth
Global Vel Dist=  1 , 1 , 1
Global Log Level= 0
CheckData=True
Encroach Param= -1, 0, 0, 0
BEGIN DESCRIPTION:
Multiple Run
END DESCRIPTION:

--- Elm 13.f01 (steady flow) ---

Flow Title=Multiple
Number of Profiles=7
Profile Names=10-year,25-year,50-year,1pct_min,100-year,1pct_plu,500-year
River Rch & RM= Elm 13,Reach-1,6208
     304     428     531     409     655     901    1010
River Rch & RM= Elm 13,Reach-1,3848
     411     587     736     572     916    1260    1440
Boundary for River Rch & Prof#=Elm 13,Reach-1,1
Up Type=0
Dn Type=3
Dn Slope=0.005
Boundary for River Rch & Prof#=Elm 13,Reach-1,2
Up Type=0
Dn Type=3
Dn Slope=0.005
Boundary for River Rch & Prof#=Elm 13,Reach-1,3
Up Type=0
Dn Type=3
Dn Slope=0.005
Boundary for River Rch & Prof#=Elm 13,Reach-1,4
Up Type=0
Dn Type=3
Dn Slope=0.005
Boundary for River Rch & Prof#=Elm 13,Reach-1,5
Up Type=0
Dn Type=3
Dn Slope=0.005
Boundary for River Rch & Prof#=Elm 13,Reach-1,6
Up Type=0
Dn Type=3
Dn Slope=0.005
Boundary for River Rch & Prof#=Elm 13,Reach-1,7
Up Type=0
Dn Type=3
Dn Slope=0.005

--- Elm 13.g01 (geometry) ---

Geom Title=Existing Conditions

River Reach=Elm 13,Reach-1
Reach XY= 30
      1477805.00      6788038.00      1478001.87      6787836.37
      1477955.38      6787653.27      1478058.51      6787346.48
      1478299.81      6787182.56      1478310.47      6787035.56
      1478451.54      6786886.50      1478412.53      6786737.99
      1478465.75      6786628.32      1478852.71      6786343.84
      1479068.30      6786274.60      1479346.87      6785994.07
      1479410.52      6785785.57      1479581.27      6785561.12
      1479952.07      6785380.03      1479953.78      6785048.50
      1479901.81      6784896.35      1479807.01      6784832.32
      1479806.62      6784599.83      1479956.50      6784491.63
      1480071.79      6784471.56      1480210.59      6784243.61
      1480382.92      6784102.80      1480344.24      6784038.13
      1480160.94      6784035.74      1479860.29      6783890.67
      1479860.39      6783785.58      1480051.86      6783586.36
      1480011.95      6783487.88      1480055.00      6783438.00

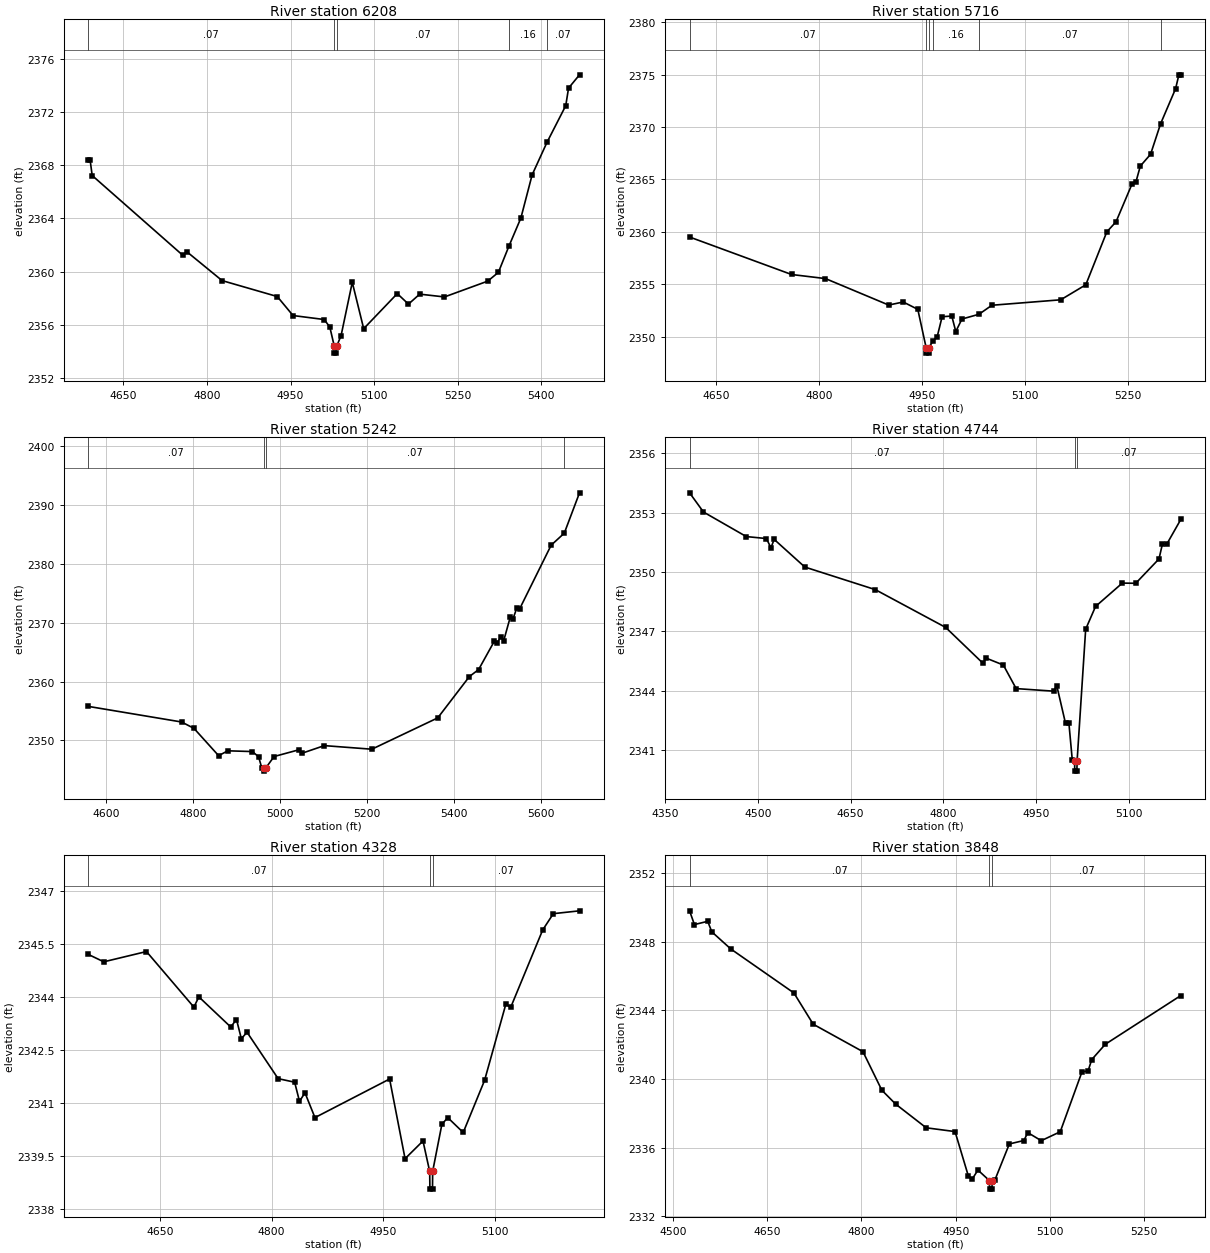
Type RM Length L Ch R = 1,6208,492,492,492
BEGIN DESCRIPTION:
321
END DESCRIPTION:
XS GIS Cut Line= 3
      1478254.98      6787937.98      1477955.38      6787653.27
      1477490.62      6787590.35
#Sta/Elev= 30
  4586.7 2368.39  4590.1 2368.39  4593.8 2367.23  4756.4 2361.23  4763.6 2361.50
  4827.1 2359.32  4926.2 2358.12  4954.5 2356.69  5010.5 2356.39  5020.6 2355.82
  5028.7 2354.36  5028.9 2353.86  5032.4 2353.86  5032.7 2354.36  5040.8 2355.18
  5060.9 2359.19  5081.4 2355.70  5141.7 2358.34  5161.8 2357.55  5182.0 2358.30
  5226.5 2358.09  5304.2 2359.28  5323.3 2359.94  5342.2 2361.91  5363.7 2364.03
  5383.9 2367.28  5410.5 2369.72  5444.3 2372.49  5449.3 2373.81  5469.0 2374.81
#Mann=5,-1,0
  4586.7    0.07       0  5028.7    0.07       0  5032.7    0.07       0
  5342.2    0.16       0  5410.5    0.07       0
Bank Sta=5028.7,5032.7
Exp/Cntr=0.3,0.1

Type RM Length L Ch R = 1,5716,474,474,474
BEGIN DESCRIPTION:
320
END DESCRIPTION:
XS GIS Cut Line= 3
      1478454.99      6787537.99      1478181.86      6787261.71
      1477905.03      6787088.02
#Sta/Elev= 30
  4611.5 2359.52  4760.0 2355.95  4809.4 2355.56  4901.4 2353.04  4922.6 2353.33
  4943.8 2352.63  4956.0 2348.96  4956.2 2348.46  4959.7 2348.46  4960.0 2348.96
  4965.5 2349.60  4972.1 2350.04  4979.2 2351.93  4993.3 2351.99  4999.1 2350.52
  5008.1 2351.71  5032.8 2352.16  5051.7 2353.02  5151.9 2353.54  5188.4 2354.97
  5219.0 2360.01  5232.4 2360.97  5255.5 2364.54  5261.4 2364.77  5267.8 2366.28
  5282.7 2367.40  5297.3 2370.31  5319.2 2373.66  5323.9 2374.97  5326.8 2374.97
#Mann=6,-1,0
  4611.5    0.07       0  4956.0    0.07       0  4960.0    0.07       0
  4965.5    0.16       0  5032.8    0.07       0  5297.3    0.16       0
Bank Sta=4956,4960
Exp/Cntr=0.3,0.1

Type RM Length L Ch R = 1,5242,498,498,498
BEGIN DESCRIPTION:
319
END DESCRIPTION:
XS GIS Cut Line= 3
      1478757.99      6787208.43      1478435.42      6786908.15
      1477855.00      6786538.00
#Sta/Elev= 30
  4559.3 2355.79  4773.9 2353.14  4802.3 2352.06  4859.0 2347.42  4880.0 2348.25
  4936.6 2348.12  4950.8 2347.24  4958.1 2345.36  4963.0 2345.30  4963.2 2344.80
  4967.0 2345.30  4986.5 2347.28  5044.4 2348.44  5050.3 2347.83  5101.9 2349.13
  5211.1 2348.52  5362.6 2353.84  5435.4 2360.86  5456.5 2362.04  5492.9 2366.89
  5498.8 2366.54  5508.1 2367.65  5514.1 2366.91  5529.3 2370.96  5535.2 2370.60
  5544.5 2372.51  5550.5 2372.30  5623.2 2383.15  5653.4 2385.19  5688.4 2392.04
#Mann=4,-1,0
  4559.3    0.07       0  4963.0    0.07       0  4967.0    0.07       0
  5653.4    0.16       0
Bank Sta=4963,4967
Exp/Cntr=0.3,0.1

Type RM Length L Ch R = 1,4744,416,416,416
BEGIN DESCRIPTION:
318
END DESCRIPTION:
XS GIS Cut Line= 3
      1478755.00      6787088.01      1478595.32      6786498.76
      1478505.00      6786338.00
#Sta/Elev= 30
  4389.5 2354.00  4412.0 2353.03  4481.3 2351.79  4513.8 2351.69  4521.2 2351.22
  4526.3 2351.65  4576.0 2350.25  4690.0 2349.11  4803.9 2347.20  4864.2 2345.39
  4869.3 2345.65  4897.2 2345.30  4917.9 2344.11  4978.5 2343.98  4983.7 2344.25
  4997.8 2342.35  5003.3 2342.35  5008.7 2340.51  5012.5 2340.44  5012.7 2339.94
  5016.2 2339.94  5016.5 2340.44  5030.4 2347.11  5046.4 2348.26  5089.7 2349.44
  5111.4 2349.43  5149.0 2350.66  5154.7 2351.43  5161.5 2351.40  5184.4 2352.66
#Mann=3,-1,0
  4389.5    0.07       0  5012.5    0.07       0  5016.5    0.07       0
Bank Sta=5012.5,5016.5
Exp/Cntr=0.3,0.1

Type RM Length L Ch R = 1,4328,480,480,480
BEGIN DESCRIPTION:
317
END DESCRIPTION:
XS GIS Cut Line= 3
      1479289.66      6786583.42      1478945.35      6786298.84
      1478779.99      6786162.99
#Sta/Elev= 30
  4553.3 2345.20  4574.2 2344.99  4631.6 2345.28  4695.4 2343.71  4702.1 2344.00
  4744.9 2343.15  4752.7 2343.36  4759.2 2342.82  4766.9 2343.00  4808.7 2341.69
  4830.9 2341.59  4837.4 2341.05  4844.8 2341.29  4858.2 2340.59  4958.6 2341.68
  4979.4 2339.43  5003.5 2339.93  5012.5 2339.07  5012.8 2338.57  5016.3 2338.57
  5016.5 2339.07  5028.9 2340.40  5036.8 2340.59  5057.6 2340.17  5086.3 2341.64
  5115.0 2343.80  5121.4 2343.70  5164.5 2345.89  5178.8 2346.35  5214.0 2346.43
#Mann=3,-1,0
  4553.3    0.07       0  5012.5    0.07       0  5016.5    0.07       0
Bank Sta=5012.5,5016.5
Exp/Cntr=0.3,0.1

Type RM Length L Ch R = 1,3848,476,476,476
BEGIN DESCRIPTION:
316
END DESCRIPTION:
XS GIS Cut Line= 3
      1479555.00      6786438.00      1479305.65      6786035.60
      1479038.98      6785880.90
#Sta/Elev= 30
  4526.6 2349.79  4534.3 2348.99  4555.5 2349.18  4561.9 2348.57  4592.2 2347.57
  4692.6 2345.01  4723.3 2343.19  4802.5 2341.59  4832.5 2339.35  4854.5 2338.54
  4903.1 2337.16  4949.0 2336.94  4970.3 2334.34  4976.1 2334.16  4985.4 2334.70
  5003.6 2334.09  5003.9 2333.59  5007.8 2333.59  5008.1 2334.09  5012.3 2334.11
  5035.4 2336.22  5058.6 2336.42  5064.7 2336.88  5086.2 2336.41  5116.4 2336.93
  5151.0 2340.42  5160.7 2340.47  5166.5 2341.13  5188.0 2342.02  5308.3 2344.86
#Mann=3,-1,0
  4526.6    0.07       0  5003.6    0.07       0  5008.1    0.07       0
Bank Sta=5003.6,5008.1
Exp/Cntr=0.3,0.1

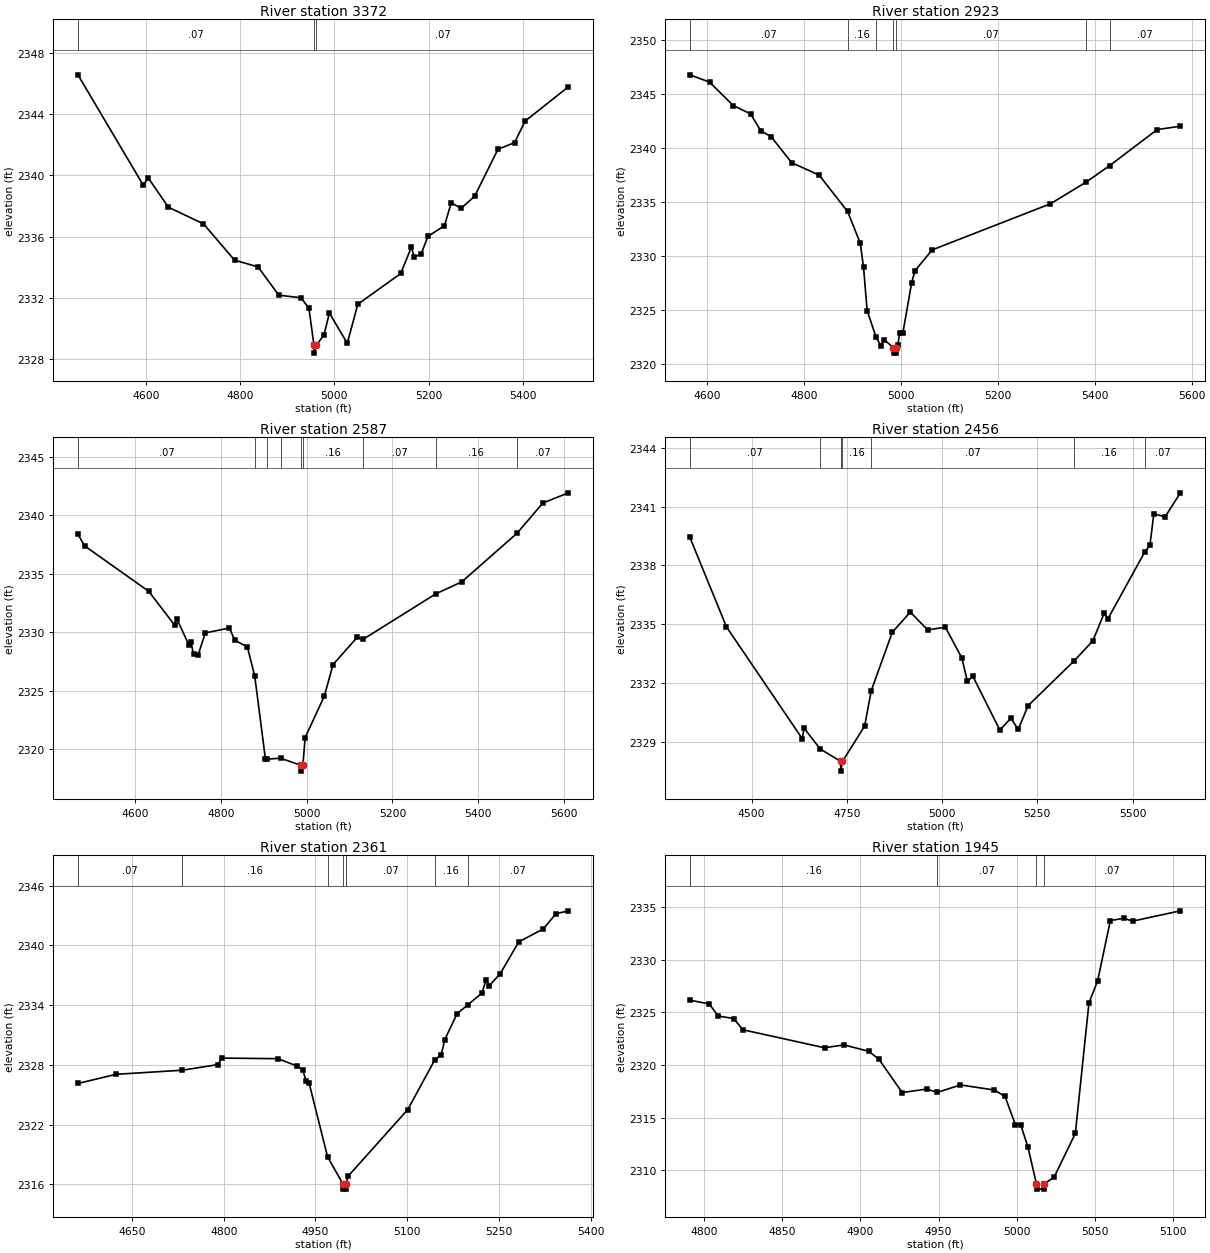
Type RM Length L Ch R = 1,3372,449,449,449
BEGIN DESCRIPTION:
315
END DESCRIPTION:
XS GIS Cut Line= 3
      1480055.01      6785838.00      1479544.22      6785647.68
      1479154.99      6785337.99
#Sta/Elev= 30
  4454.9 2346.57  4593.6 2339.37  4604.3 2339.84  4647.0 2337.93  4721.7 2336.84
  4787.7 2334.47  4837.7 2334.03  4881.8 2332.18  4928.6 2332.02  4945.8 2331.34
  4956.6 2328.90  4957.0 2328.40  4961.3 2328.90  4977.8 2329.59  4989.3 2331.02
  5027.3 2329.04  5049.7 2331.59  5141.0 2333.60  5163.4 2335.31  5169.8 2334.68
  5184.2 2334.86  5198.7 2336.02  5233.9 2336.72  5248.3 2338.22  5269.1 2337.85
  5298.0 2338.64  5347.6 2341.71  5382.8 2342.14  5405.3 2343.55  5497.4 2345.79
#Mann=3,-1,0
  4454.9    0.07       0  4956.6    0.07       0  4961.3    0.07       0
Bank Sta=4956.6,4961.3
Exp/Cntr=0.3,0.1

Type RM Length L Ch R = 1,2923,336,336,336
BEGIN DESCRIPTION:
314
END DESCRIPTION:
XS GIS Cut Line= 5
      1480176.73      6785703.63      1480009.24      6785537.16
      1479875.27      6785388.31      1479806.04      6785322.81
      1479332.87      6785234.22
#Sta/Elev= 30
  4563.6 2346.74  4604.2 2346.07  4653.6 2343.89  4689.0 2343.13  4710.2 2341.56
  4731.4 2341.03  4773.9 2338.62  4830.4 2337.48  4889.4 2334.11  4915.6 2331.18
  4922.3 2328.96  4929.8 2324.94  4948.4 2322.48  4958.2 2321.69  4964.9 2322.27
  4984.2 2321.52  4984.5 2321.02  4988.6 2321.02  4988.9 2321.52  4993.3 2321.75
  4996.8 2322.89  5003.6 2322.89  5021.7 2327.52  5028.5 2328.63  5064.1 2330.56
  5308.3 2334.82  5382.3 2336.83  5430.7 2338.35  5528.9 2341.68  5576.7 2341.99
#Mann=7,-1,0
  4563.6    0.07       0  4889.4    0.16       0  4948.4    0.07       0
  4984.2    0.07       0  4988.9    0.07       0  5382.3    0.16       0
  5430.7    0.07       0
Bank Sta=4984.2,4988.9
Exp/Cntr=0.3,0.1

Type RM Length L Ch R = 1,2587,131,131,131
BEGIN DESCRIPTION:
760
END DESCRIPTION:
XS GIS Cut Line= 6
      1480453.44      6785247.78      1480121.12      6785149.32
      1480040.90      6785096.46      1479888.82      6785143.69
      1479811.82      6785199.86      1479365.40      6785207.09
#Sta/Elev= 30
  4466.6 2338.38  4482.0 2337.39  4631.8 2333.50  4691.9 2330.62  4697.1 2331.16
  4725.2 2328.93  4730.4 2329.16  4736.1 2328.11  4746.6 2328.04  4763.6 2329.95
  4819.6 2330.37  4832.5 2329.32  4861.7 2328.75  4878.8 2326.27  4903.8 2319.17
  4907.4 2319.17  4939.2 2319.24  4986.4 2318.64  4986.7 2318.14  4991.1 2318.64
  4996.4 2321.01  5041.1 2324.55  5061.5 2327.25  5117.4 2329.56  5131.8 2329.41
  5300.6 2333.28  5361.8 2334.32  5490.5 2338.47  5550.7 2341.05  5610.3 2341.92
#Mann=9,-1,0
  4466.6    0.07       0  4878.8    0.16       0  4907.4    0.07       0
  4939.2    0.16       0  4986.4    0.07       0  4991.1    0.16       0
  5131.8    0.07       0  5300.6    0.16       0  5490.5    0.07       0
Bank Sta=4986.4,4991.1
Exp/Cntr=0.3,0.1

Type RM Length L Ch R = 1,2456,95,95,95
BEGIN DESCRIPTION:
759
END DESCRIPTION:
XS GIS Cut Line= 6
      1480570.15      6784981.89      1480131.87      6784936.74
      1479920.76      6785002.71      1479828.40      6785122.85
      1479806.08      6785180.38      1479395.34      6785185.38
#Sta/Elev= 30
  4338.1 2339.43  4434.1 2334.86  4633.0 2329.15  4638.0 2329.68  4680.3 2328.62
  4733.8 2327.99  4734.1 2327.49  4738.7 2327.99  4796.8 2329.79  4814.2 2331.60
  4869.4 2334.58  4916.7 2335.61  4962.3 2334.70  5008.5 2334.84  5052.0 2333.27
  5066.5 2332.07  5081.0 2332.33  5151.6 2329.59  5180.7 2330.19  5199.9 2329.62
  5225.7 2330.83  5345.1 2333.09  5395.7 2334.14  5425.2 2335.54  5435.7 2335.28
  5532.3 2338.69  5545.7 2339.03  5555.7 2340.62  5585.7 2340.48  5625.4 2341.70
#Mann=7,-1,0
  4338.1    0.07       0  4680.3    0.16       0  4733.8    0.07       0
  4738.7    0.16       0  4814.2    0.07       0  5345.1    0.16       0
  5532.3    0.07       0
Bank Sta=4733.8,4738.7
Exp/Cntr=0.3,0.1

Type RM Length L Ch R = 1,2361,416,416,416
BEGIN DESCRIPTION:
313
END DESCRIPTION:
XS GIS Cut Line= 4
      1480309.65      6784756.70      1480044.04      6784891.46
      1479905.12      6784912.88      1479544.51      6784960.19
#Sta/Elev= 30
  4561.6 2326.13  4624.1 2327.05  4732.2 2327.46  4791.0 2328.03  4796.6 2328.68
  4888.8 2328.62  4919.2 2327.90  4929.3 2327.50  4934.8 2326.33  4939.8 2326.13
  4969.8 2318.76  4995.1 2316.01  4995.4 2315.51  4999.6 2315.51  5000.0 2316.01
  5003.0 2316.78  5101.0 2323.51  5145.0 2328.49  5155.6 2329.02  5161.5 2330.54
  5181.7 2333.16  5199.3 2334.03  5222.0 2335.21  5229.3 2336.55  5234.3 2335.95
  5252.3 2337.18  5282.5 2340.36  5322.9 2341.67  5343.0 2343.18  5363.7 2343.48
#Mann=7,-1,0
  4561.6    0.07       0  4732.2    0.16       0  4969.8    0.07       0
  4995.1    0.07       0  5000.0    0.07       0  5145.0    0.16       0
  5199.3    0.07       0
Bank Sta=4995.1,5000
Exp/Cntr=0.3,0.1

Type RM Length L Ch R = 1,1945,492,492,492
BEGIN DESCRIPTION:
312
END DESCRIPTION:
XS GIS Cut Line= 3
      1480029.70      6784689.75      1479848.47      6784585.26
      1479755.03      6784538.02
#Sta/Elev= 30
  4790.8 2326.17  4803.2 2325.81  4808.9 2324.67  4818.9 2324.42  4824.7 2323.36
  4877.0 2321.65  4889.4 2321.92  4905.2 2321.32  4911.7 2320.58  4926.7 2317.40
  4942.5 2317.73  4949.1 2317.41  4964.0 2318.12  4985.6 2317.64  4992.5 2317.03
  4999.1 2314.36  5002.5 2314.36  5007.2 2312.20  5012.6 2308.73  5013.0 2308.23
  5017.2 2308.23  5017.5 2308.73  5023.9 2309.36  5037.5 2313.52  5046.2 2325.89
  5051.8 2328.03  5059.9 2333.72  5068.5 2333.95  5074.1 2333.67  5104.7 2334.65
#Mann=4,-1,0
  4790.8    0.16       0  4949.1    0.07       0  5012.6    0.07       0
  5017.5    0.07       0
Bank Sta=5012.6,5017.5
Exp/Cntr=0.3,0.1

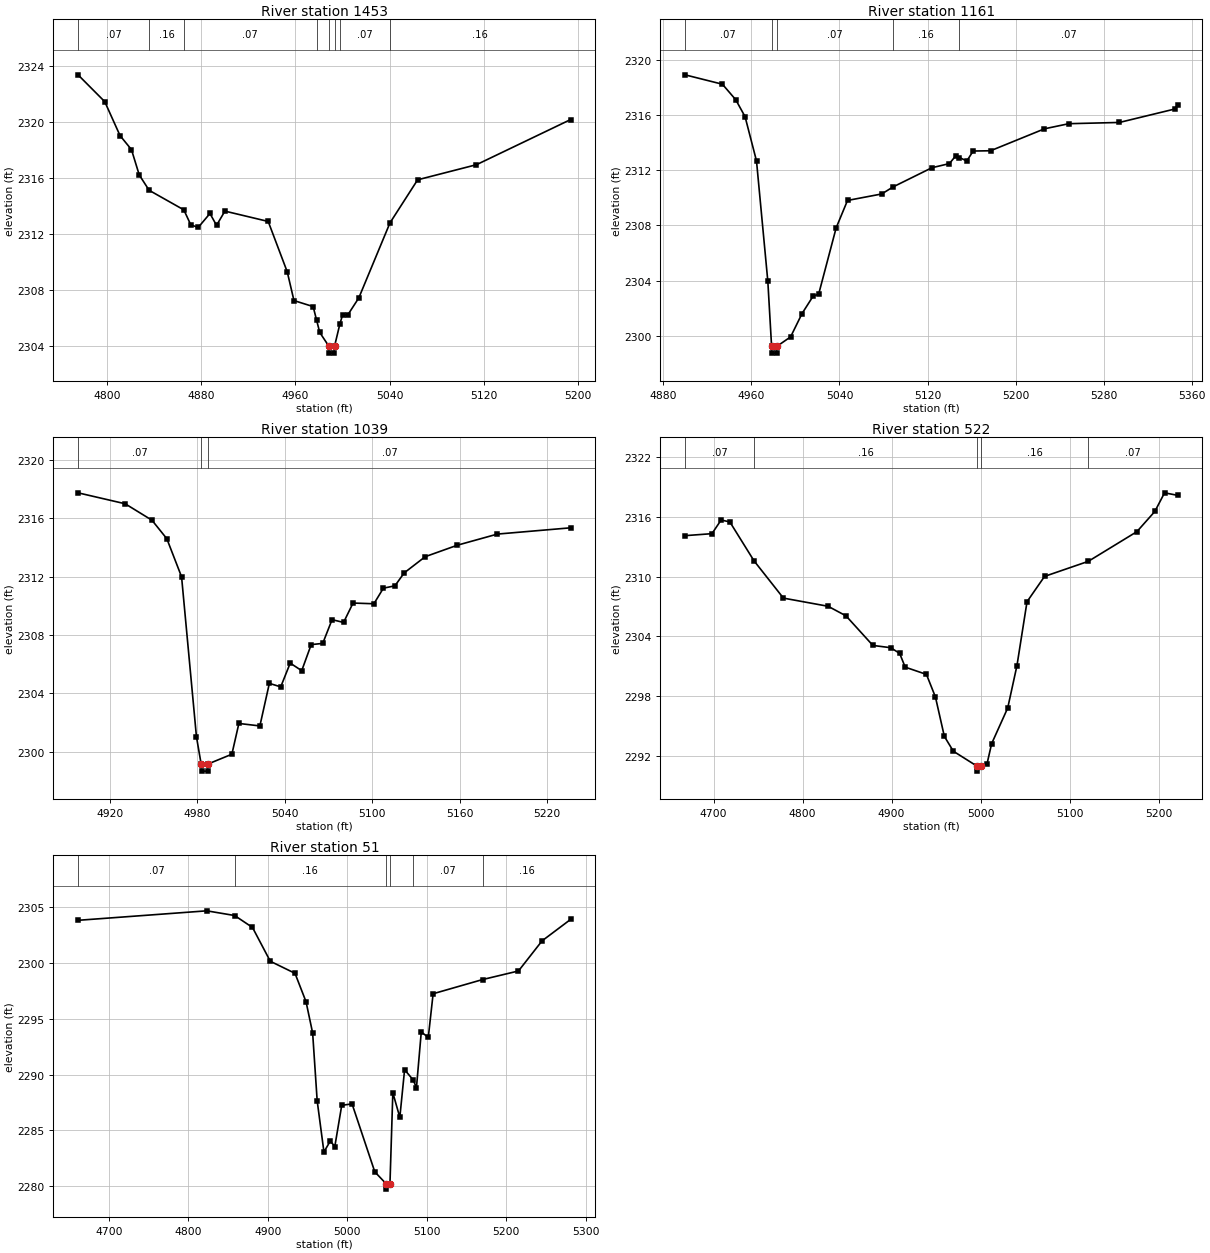
Type RM Length L Ch R = 1,1453,292,292,292
BEGIN DESCRIPTION:
311
END DESCRIPTION:
XS GIS Cut Line= 3
      1480304.99      6784487.97      1480198.76      6784289.85
      1480004.97      6784288.00
#Sta/Elev= 30
  4775.2 2323.40  4797.9 2321.48  4810.9 2319.05  4820.6 2318.05  4827.2 2316.24
  4835.6 2315.14  4865.1 2313.74  4871.0 2312.67  4877.3 2312.48  4887.3 2313.48
  4892.9 2312.63  4900.0 2313.65  4936.8 2312.91  4953.0 2309.30  4958.7 2307.25
  4975.0 2306.82  4977.9 2305.86  4980.6 2304.97  4988.3 2303.99  4988.7 2303.49
  4992.9 2303.49  4993.2 2303.99  4997.7 2305.57  5000.0 2306.22  5004.4 2306.22
  5013.8 2307.44  5040.3 2312.81  5063.8 2315.89  5113.8 2316.97  5193.8 2320.20
#Mann=8,-1,0
  4775.2    0.07       0  4835.6    0.16       0  4865.1    0.07       0
  4977.9    0.16       0  4988.3    0.07       0  4993.2    0.16       0
  4997.7    0.07       0  5040.3    0.16       0
Bank Sta=4988.3,4993.2
Exp/Cntr=0.3,0.1

Type RM Length L Ch R = 1,1161,122,122,122
BEGIN DESCRIPTION:
837
END DESCRIPTION:
XS GIS Cut Line= 3
      1480477.84      6784062.11      1480282.53      6784113.65
      1480069.12      6784235.21
#Sta/Elev= 30
  4899.6 2318.91  4933.6 2318.23  4945.7 2317.11  4954.2 2315.88  4964.6 2312.67
  4974.9 2303.94  4978.3 2299.25  4978.7 2298.75  4982.9 2298.75  4983.3 2299.25
  4995.6 2299.93  5006.0 2301.62  5015.9 2302.86  5021.1 2303.03  5037.0 2307.83
  5047.3 2309.81  5078.4 2310.28  5088.7 2310.79  5124.0 2312.18  5139.9 2312.48
  5145.6 2313.04  5149.0 2312.92  5155.7 2312.67  5161.5 2313.39  5177.3 2313.41
  5226.3 2315.00  5248.4 2315.37  5294.4 2315.46  5344.5 2316.43  5347.2 2316.74
#Mann=5,-1,0
  4899.6    0.07       0  4978.3    0.07       0  4983.3    0.07       0
  5088.7    0.16       0  5149.0    0.07       0
Bank Sta=4978.3,4983.3
Exp/Cntr=0.3,0.1

Type RM Length L Ch R = 1,1039,517,517,517
BEGIN DESCRIPTION:
310
END DESCRIPTION:
XS GIS Cut Line= 3
      1480304.99      6783938.04      1480287.57      6784038.24
      1480105.03      6784187.98
#Sta/Elev= 30
  4898.3 2317.75  4930.6 2317.00  4949.0 2315.87  4959.2 2314.60  4969.3 2311.99
  4979.5 2301.02  4982.7 2299.16  4983.1 2298.66  4987.3 2298.66  4987.7 2299.16
  5003.8 2299.82  5008.6 2301.93  5023.0 2301.76  5029.5 2304.68  5037.3 2304.44
  5043.8 2306.07  5051.7 2305.55  5058.2 2307.34  5066.1 2307.42  5072.5 2309.05
  5080.4 2308.86  5086.9 2310.19  5101.2 2310.14  5107.7 2311.21  5115.6 2311.37
  5122.0 2312.26  5136.4 2313.37  5158.5 2314.16  5185.9 2314.92  5236.1 2315.35
#Mann=3,-1,0
  4898.3    0.07       0  4982.7    0.07       0  4987.7    0.07       0
Bank Sta=4982.7,4987.7
Exp/Cntr=0.3,0.1

Type RM Length L Ch R = 1,522,471,471,471
BEGIN DESCRIPTION:
758
END DESCRIPTION:
XS GIS Cut Line= 3
      1480185.13      6783819.62      1479851.94      6783851.09
      1479640.88      6783908.48
#Sta/Elev= 30
  4667.9 2314.12  4698.2 2314.32  4708.5 2315.69  4718.3 2315.50  4745.5 2311.59
  4778.5 2307.85  4828.7 2307.03  4848.8 2306.07  4879.0 2303.10  4899.1 2302.87
  4909.1 2302.30  4915.3 2300.92  4939.2 2300.19  4949.3 2297.92  4959.3 2293.97
  4969.4 2292.48  4996.0 2290.98  4996.4 2290.48  5001.0 2290.98  5007.2 2291.19
  5012.4 2293.23  5030.5 2296.82  5040.9 2301.08  5052.2 2307.49  5071.9 2310.03
  5121.0 2311.54  5175.6 2314.52  5195.8 2316.55  5206.7 2318.42  5221.3 2318.17
#Mann=5,-1,0
  4667.9    0.07       0  4745.5    0.16       0  4996.0    0.07       0
  5001.0    0.16       0  5121.0    0.07       0
Bank Sta=4996,5001
Exp/Cntr=0.3,0.1

Type RM Length L Ch R = 1,51,0,0,0
BEGIN DESCRIPTION:
309
END DESCRIPTION:
XS GIS Cut Line= 4
      1480320.29      6783628.92      1480016.32      6783473.11
      1479970.74      6783481.08      1479779.97      6783613.02
#Sta/Elev= 30
  4661.3 2303.82  4823.3 2304.67  4858.3 2304.25  4880.8 2303.18  4903.2 2300.15
  4934.3 2299.07  4948.2 2296.52  4956.5 2293.72  4962.2 2287.65  4970.7 2283.06
  4978.7 2284.04  4984.4 2283.55  4993.1 2287.24  5006.1 2287.37  5034.7 2281.28
  5048.7 2280.23  5049.1 2279.73  5053.8 2280.23  5057.4 2288.37  5066.2 2286.16
  5072.2 2290.43  5083.1 2289.51  5087.1 2288.81  5093.2 2293.82  5102.0 2293.32
  5108.1 2297.24  5170.3 2298.51  5215.5 2299.28  5245.2 2301.98  5281.1 2303.90
#Mann=6,-1,0
  4661.3    0.07       0  4858.3    0.16       0  5048.7    0.07       0
  5053.8    0.16       0  5083.1    0.07       0  5170.3    0.16       0
Bank Sta=5048.7,5053.8
Exp/Cntr=0.3,0.1

Chan Stop Cuts=-1