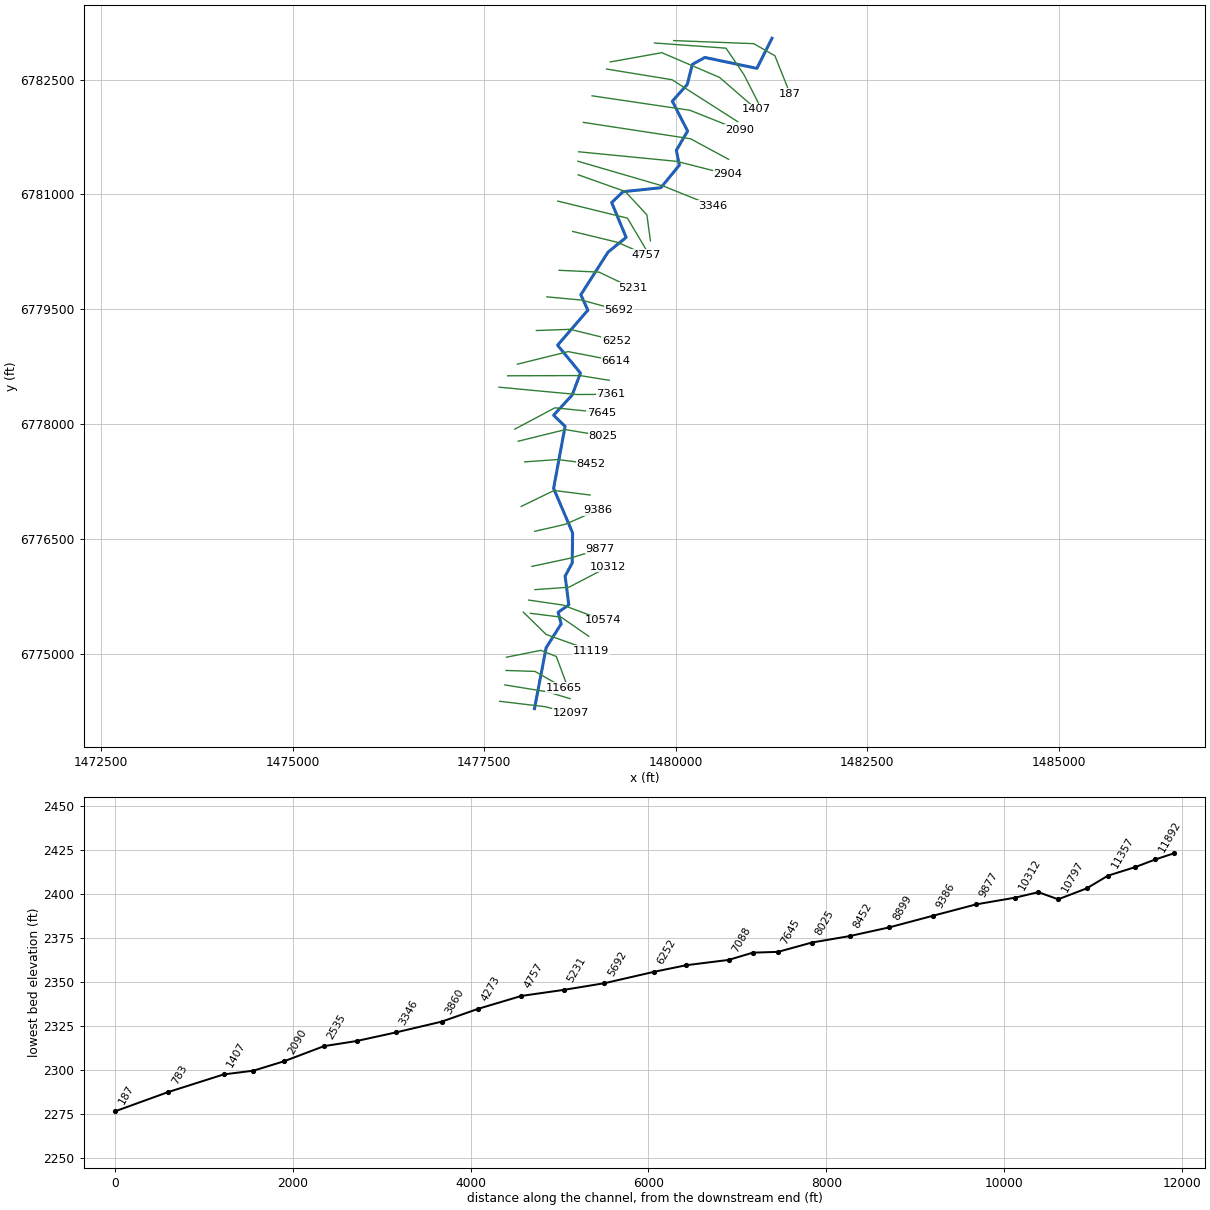
--- Elm 14.prj (project) ---

Proj Title=Elm 14 Base Level Engineering
Current Plan=p01
Default Exp/Contr=0.3,0.1
English Units
Geom File=g01
Flow File=f01
Plan File=p01
BEGIN DESCRIPTION:
Elm 14
END DESCRIPTION:

--- Elm 14.p01 (plan) ---

Plan Title=Multiple Run
Short Identifier=Multiple
Geom File=g01
Flow File=f01
Subcritical Flow
K Sum by GR= 0
Std Step Tol= 0.01
Critical Tol= 0.01
Num of Std Step Trials= 20
Max Error Tol= 0.3
Flow Tol Ratio= 0.001
Split Flow NTrial= 30
Split Flow Tol= 0.02
Split Flow Ratio= 0.02
Log Output Level= 0
Friction Slope Method= 1
Unsteady Friction Slope Method= 2
Unsteady Bridges Friction Slope Method= 1
Parabolic Critical Depth
Global Vel Dist=  1 , 1 , 1
Global Log Level= 0
CheckData=True
Encroach Param= -1, 0, 0, 0
BEGIN DESCRIPTION:
Multiple Run
END DESCRIPTION:

--- Elm 14.f01 (steady flow) ---

Flow Title=Multiple
Number of Profiles=7
Profile Names=10-year,25-year,50-year,1pct_min,100-year,1pct_plu,500-year
River Rch & RM= Elm 14,Reach-1,12097
     326     460     573     442     708     975    1100
River Rch & RM= Elm 14,Reach-1,3346
     460     662     836     653    1050    1440    1660
Boundary for River Rch & Prof#=Elm 14,Reach-1,1
Up Type=0
Dn Type=3
Dn Slope=0.005
Boundary for River Rch & Prof#=Elm 14,Reach-1,2
Up Type=0
Dn Type=3
Dn Slope=0.005
Boundary for River Rch & Prof#=Elm 14,Reach-1,3
Up Type=0
Dn Type=3
Dn Slope=0.005
Boundary for River Rch & Prof#=Elm 14,Reach-1,4
Up Type=0
Dn Type=3
Dn Slope=0.005
Boundary for River Rch & Prof#=Elm 14,Reach-1,5
Up Type=0
Dn Type=3
Dn Slope=0.005
Boundary for River Rch & Prof#=Elm 14,Reach-1,6
Up Type=0
Dn Type=3
Dn Slope=0.005
Boundary for River Rch & Prof#=Elm 14,Reach-1,7
Up Type=0
Dn Type=3
Dn Slope=0.005

--- Elm 14.g01 (geometry) ---

Geom Title=Existing Conditions

River Reach=Elm 14,Reach-1
Reach XY= 30
      1478155.00      6774288.00      1478307.06      6775082.15
      1478503.01      6775393.89      1478464.02      6775545.02
      1478603.02      6775643.67      1478554.89      6776017.91
      1478647.24      6776188.08      1478652.94      6776582.14
      1478404.77      6777162.93      1478554.67      6777972.97
      1478404.60      6778117.73      1478646.98      6778381.66
      1478755.39      6778667.87      1478456.97      6779032.10
      1478851.90      6779489.65      1478760.06      6779690.29
      1479115.76      6780247.68      1479351.63      6780439.28
      1479162.76      6780894.17      1479310.85      6781035.94
      1479805.00      6781088.00      1480045.88      6781381.24
      1480006.90      6781576.05      1480153.90      6781827.45
      1479954.59      6782217.87      1480149.53      6782435.56
      1480215.52      6782697.77      1480380.00      6782788.41
      1481058.43      6782645.79      1481255.00      6783038.00

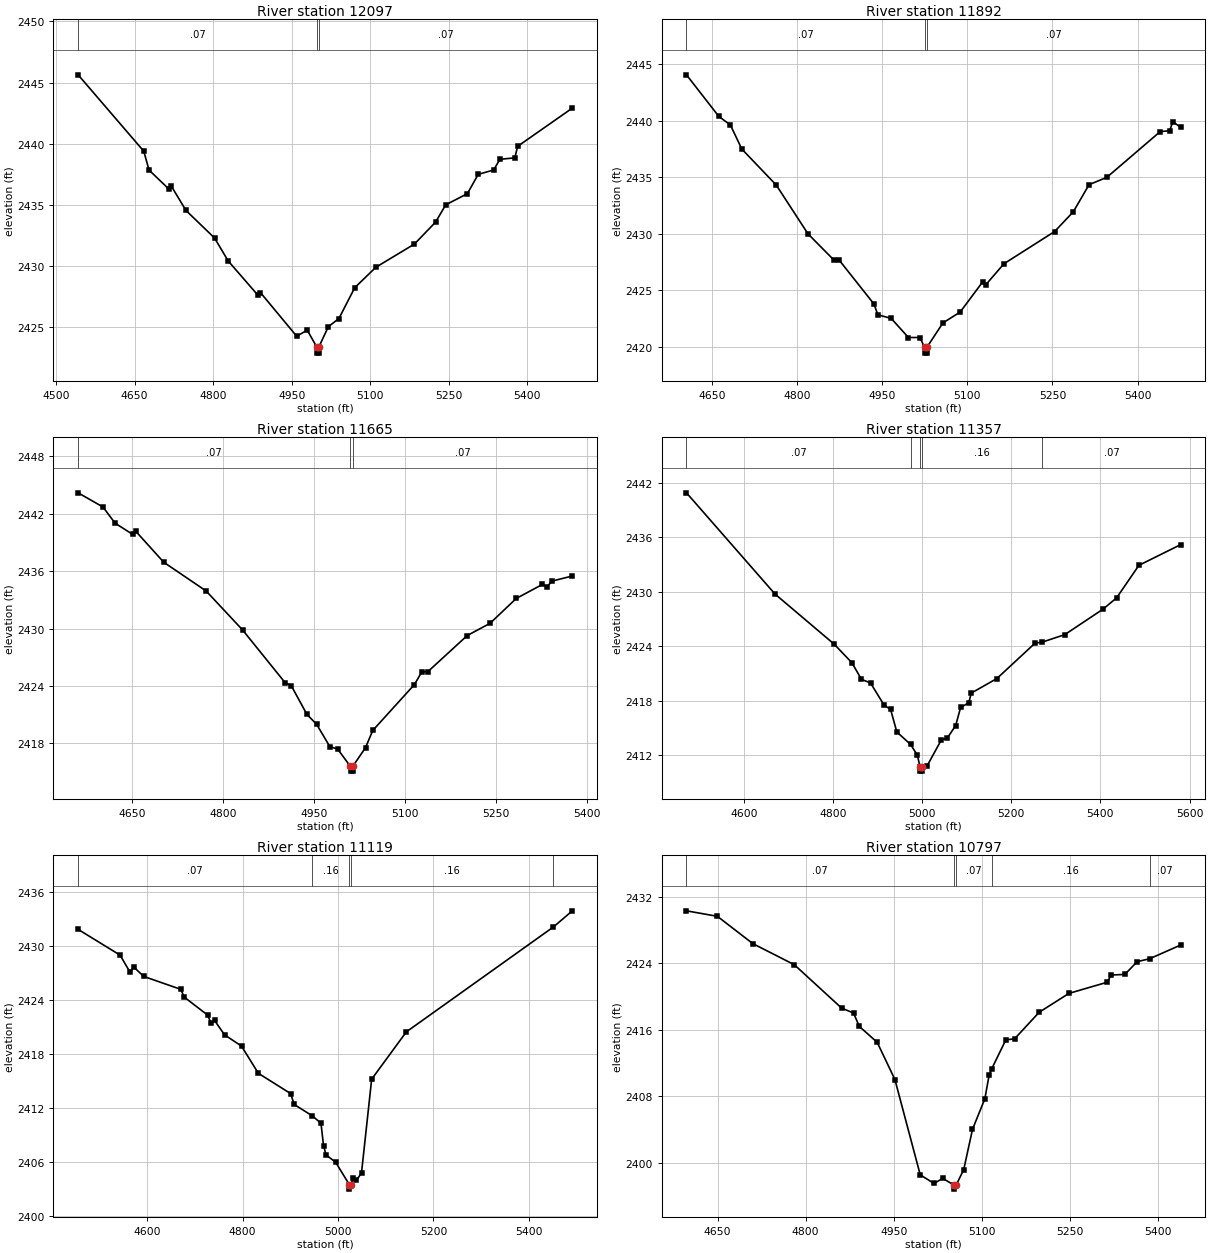
Type RM Length L Ch R = 1,12097,205,205,205
BEGIN DESCRIPTION:
elmc270
END DESCRIPTION:
XS GIS Cut Line= 3
      1477700.53      6774383.75      1478297.81      6774312.58
      1478628.95      6774225.92
#Sta/Elev= 30
  4542.1 2445.63  4667.5 2439.38  4677.5 2437.84  4715.1 2436.30  4720.2 2436.52
  4748.0 2434.54  4802.7 2432.28  4828.6 2430.41  4885.2 2427.62  4890.3 2427.82
  4959.5 2424.25  4979.6 2424.75  4997.8 2423.37  4998.0 2422.87  5001.5 2422.87
  5001.8 2423.37  5019.9 2425.03  5040.1 2425.70  5070.3 2428.22  5110.6 2429.89
  5184.3 2431.79  5224.8 2433.59  5244.1 2435.00  5285.4 2435.91  5306.1 2437.49
  5335.7 2437.85  5347.4 2438.72  5376.1 2438.84  5381.3 2439.78  5485.9 2442.91
#Mann=3,-1,0
  4542.1    0.07       0  4997.8    0.07       0  5001.8    0.07       0
Bank Sta=4997.8,5001.8
Exp/Cntr=0.3,0.1

Type RM Length L Ch R = 1,11892,227,227,227
BEGIN DESCRIPTION:
elmc269
END DESCRIPTION:
XS GIS Cut Line= 3
      1477768.65      6774597.28      1478322.57      6774507.54
      1478619.66      6774417.79
#Sta/Elev= 30
  4604.6 2444.06  4661.7 2440.38  4682.0 2439.63  4702.2 2437.50  4763.0 2434.31
  4818.8 2430.01  4864.3 2427.70  4874.4 2427.65  4935.2 2423.80  4942.1 2422.85
  4965.6 2422.53  4996.0 2420.84  5016.3 2420.84  5024.4 2419.96  5024.6 2419.46
  5028.1 2419.46  5028.4 2419.96  5056.8 2422.13  5087.2 2423.09  5127.1 2425.77
  5132.2 2425.49  5164.4 2427.36  5253.8 2430.21  5286.8 2431.96  5314.5 2434.35
  5345.9 2435.00  5439.9 2439.04  5456.8 2439.12  5462.0 2439.92  5476.1 2439.42
#Mann=3,-1,0
  4604.6    0.07       0  5024.4    0.07       0  5028.4    0.07       0
Bank Sta=5024.4,5028.4
Exp/Cntr=0.3,0.1

Type RM Length L Ch R = 1,11665,308,308,308
BEGIN DESCRIPTION:
elmc268
END DESCRIPTION:
XS GIS Cut Line= 3
      1477784.12      6774786.06      1478161.65      6774773.68
      1478541.16      6774557.69
#Sta/Elev= 30
  4561.4 2444.18  4602.3 2442.70  4622.3 2441.01  4651.0 2439.85  4656.0 2440.19
  4702.4 2436.93  4772.4 2433.92  4832.4 2429.85  4902.5 2424.34  4912.5 2424.04
  4938.3 2421.04  4954.5 2419.98  4976.3 2417.65  4989.0 2417.41  5010.0 2415.60
  5010.3 2415.10  5013.8 2415.10  5014.0 2415.60  5035.0 2417.56  5046.9 2419.35
  5115.6 2424.15  5127.6 2425.46  5137.8 2425.50  5202.6 2429.27  5240.1 2430.54
  5283.3 2433.14  5326.5 2434.61  5334.2 2434.38  5342.4 2434.96  5375.8 2435.49
#Mann=3,-1,0
  4561.4    0.07       0  5010.0    0.07       0  5014.0    0.07       0
Bank Sta=5010,5014
Exp/Cntr=0.3,0.1

Type RM Length L Ch R = 1,11357,238,238,238
BEGIN DESCRIPTION:
elmc267
END DESCRIPTION:
XS GIS Cut Line= 4
      1477790.25      6774959.35      1478239.01      6775049.10
      1478440.17      6774968.64      1478591.27      6774561.58
#Sta/Elev= 30
  4471.6 2440.90  4670.2 2429.74  4802.8 2424.22  4842.8 2422.16  4864.0 2420.34
  4884.4 2419.94  4915.0 2417.48  4929.3 2417.04  4943.4 2414.54  4974.3 2413.16
  4989.6 2411.96  4995.2 2410.72  4995.5 2410.22  4999.0 2410.22  4999.2 2410.72
  5011.1 2410.78  5043.4 2413.68  5056.5 2413.86  5075.3 2415.24  5086.5 2417.24
  5104.9 2417.76  5110.3 2418.82  5167.9 2420.43  5253.2 2424.32  5270.0 2424.45
  5320.2 2425.27  5406.0 2428.08  5436.3 2429.32  5486.4 2432.91  5580.1 2435.19
#Mann=5,-1,0
  4471.6    0.07       0  4974.3    0.16       0  4995.2    0.07       0
  4999.2    0.16       0  5270.0    0.07       0
Bank Sta=4995.2,4999.2
Exp/Cntr=0.3,0.1

Type RM Length L Ch R = 1,11119,322,322,322
BEGIN DESCRIPTION:
elmc266
END DESCRIPTION:
XS GIS Cut Line= 3
      1478010.01      6775547.34      1478307.10      6775256.44
      1478890.96      6775046.37
#Sta/Elev= 30
  4455.1 2431.87  4543.1 2429.01  4564.2 2427.09  4571.4 2427.71  4592.5 2426.65
  4670.4 2425.21  4677.4 2424.36  4726.9 2422.34  4733.9 2421.42  4741.1 2421.76
  4762.2 2420.16  4797.7 2418.91  4833.0 2415.89  4900.6 2413.64  4908.2 2412.43
  4946.3 2411.16  4964.3 2410.34  4969.7 2407.86  4975.0 2406.82  4995.0 2406.02
  5023.8 2403.53  5024.0 2403.03  5027.8 2403.53  5031.1 2404.26  5038.7 2404.00
  5049.3 2404.84  5070.6 2415.24  5143.3 2420.49  5451.7 2432.14  5491.4 2433.93
#Mann=5,-1,0
  4455.1    0.07       0  4946.3    0.16       0  5023.8    0.07       0
  5027.8    0.16       0  5451.7    0.07       0
Bank Sta=5023.8,5027.8
Exp/Cntr=0.3,0.1

Type RM Length L Ch R = 1,10797,223,223,223
BEGIN DESCRIPTION:
elmc131
END DESCRIPTION:
XS GIS Cut Line= 3
      1478102.81      6775531.87      1478502.63      6775482.12
      1478863.17      6775232.35
#Sta/Elev= 30
  4597.1 2430.29  4649.7 2429.63  4710.2 2426.34  4780.7 2423.81  4861.3 2418.59
  4881.5 2418.00  4891.5 2416.38  4921.8 2414.48  4952.0 2410.00  4995.1 2398.54
  5018.6 2397.50  5033.4 2398.11  5052.4 2397.32  5052.6 2396.82  5056.4 2397.32
  5069.2 2399.18  5084.1 2404.01  5105.1 2407.68  5112.4 2410.52  5116.7 2411.27
  5140.9 2414.78  5155.7 2414.89  5197.6 2418.09  5248.3 2420.36  5313.8 2421.71
  5319.9 2422.57  5343.5 2422.64  5364.5 2424.18  5385.5 2424.52  5438.6 2426.18
#Mann=5,-1,0
  4597.1    0.07       0  5052.4    0.07       0  5056.4    0.07       0
  5116.7    0.16       0  5385.5    0.07       0
Bank Sta=5052.4,5056.4
Exp/Cntr=0.3,0.1

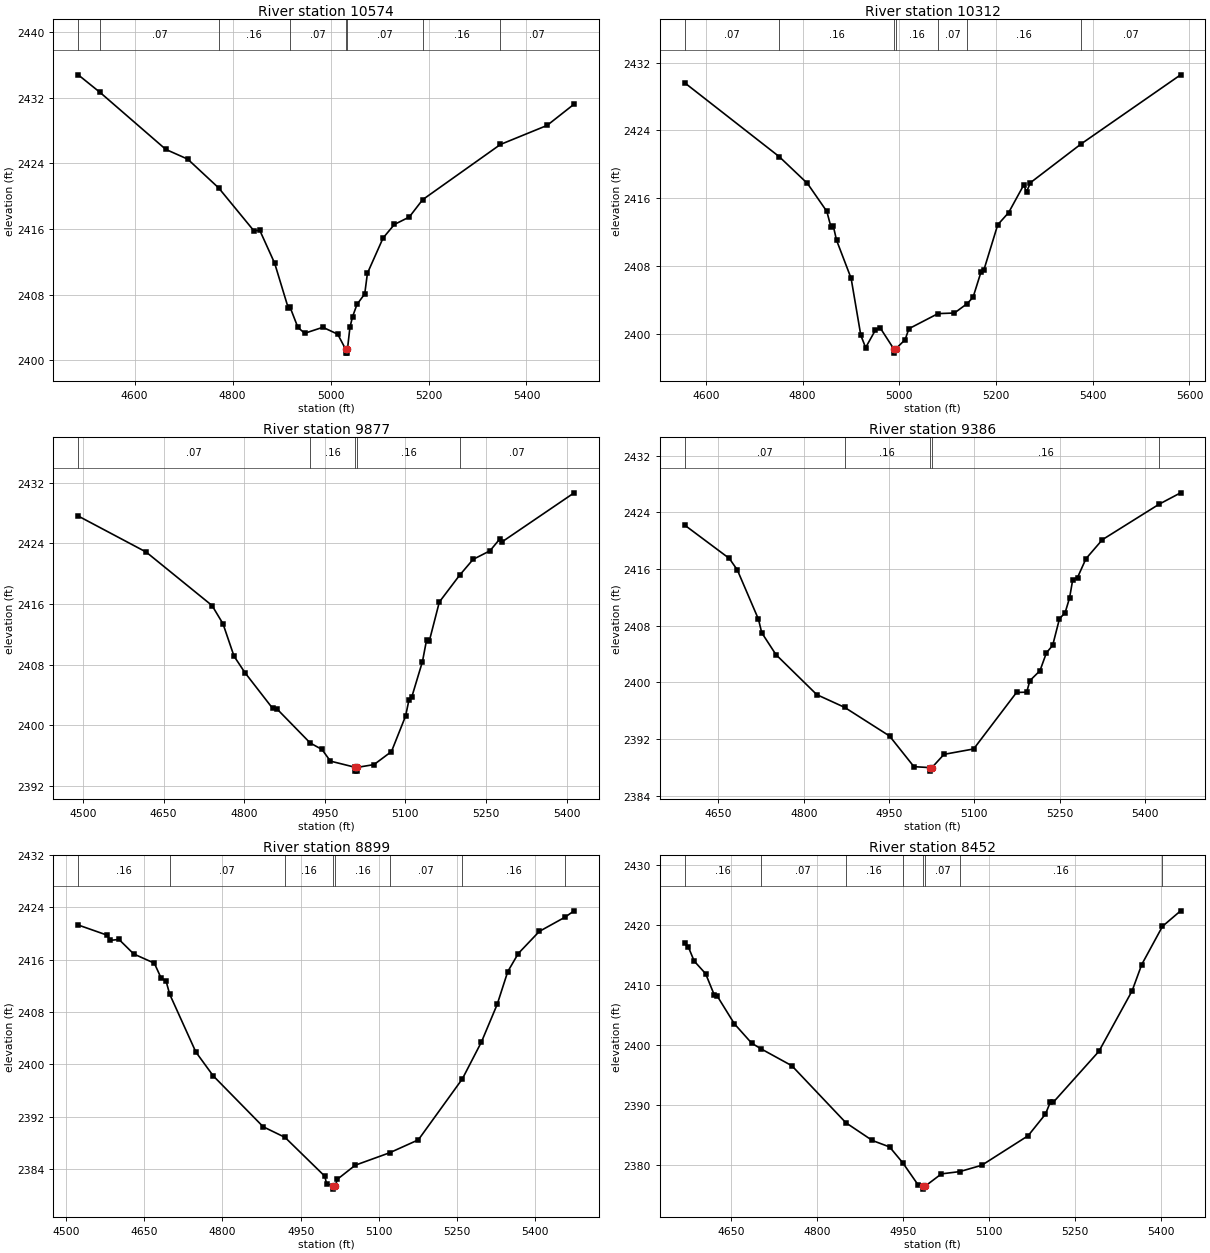
Type RM Length L Ch R = 1,10574,262,262,262
BEGIN DESCRIPTION:
elmc265
END DESCRIPTION:
XS GIS Cut Line= 3
      1478078.10      6775705.16      1478523.72      6775640.18
      1479050.31      6775443.09
#Sta/Elev= 30
  4484.7 2434.79  4529.4 2432.64  4663.5 2425.70  4708.3 2424.51  4771.5 2421.00
  4843.3 2415.78  4855.5 2415.82  4885.8 2411.82  4913.3 2406.41  4916.8 2406.53
  4933.2 2404.00  4947.1 2403.28  4984.2 2404.01  5014.5 2403.17  5030.5 2401.36
  5030.7 2400.86  5034.2 2400.86  5034.5 2401.36  5039.5 2404.01  5044.8 2405.29
  5053.9 2406.80  5069.7 2408.08  5075.2 2410.60  5107.2 2414.90  5130.3 2416.55
  5160.6 2417.45  5188.0 2419.57  5346.8 2426.30  5442.0 2428.62  5497.3 2431.22
#Mann=8,-1,0
  4484.7    0.16       0  4529.4    0.07       0  4771.5    0.16       0
  4916.8    0.07       0  5030.5    0.07       0  5034.5    0.07       0
  5188.0    0.16       0  5346.8    0.07       0
Bank Sta=5030.5,5034.5
Exp/Cntr=0.3,0.1

Type RM Length L Ch R = 1,10312,435,435,435
BEGIN DESCRIPTION:
elmc130
END DESCRIPTION:
XS GIS Cut Line= 3
      1478161.69      6775841.33      1478604.48      6775872.78
      1479120.51      6776141.26
#Sta/Elev= 30
  4556.1 2429.62  4751.4 2420.92  4810.0 2417.75  4850.1 2414.45  4858.5 2412.63
  4863.5 2412.71  4870.2 2411.05  4900.3 2406.56  4920.3 2399.85  4930.3 2398.39
  4950.4 2400.44  4960.4 2400.72  4988.5 2398.24  4988.7 2397.74  4992.5 2398.24
  5011.9 2399.32  5019.8 2400.62  5080.0 2402.40  5113.9 2402.47  5140.4 2403.58
  5152.5 2404.33  5168.9 2407.31  5174.6 2407.50  5203.5 2412.88  5226.0 2414.31
  5257.3 2417.57  5263.0 2416.75  5271.1 2417.84  5376.4 2422.43  5581.7 2430.56
#Mann=7,-1,0
  4556.1    0.07       0  4751.4    0.16       0  4988.5    0.07       0
  4992.5    0.16       0  5080.0    0.07       0  5140.4    0.16       0
  5376.4    0.07       0
Bank Sta=4988.5,4992.5
Exp/Cntr=0.3,0.1

Type RM Length L Ch R = 1,9877,491,491,491
BEGIN DESCRIPTION:
elmc129
END DESCRIPTION:
XS GIS Cut Line= 3
      1478121.45      6776144.61      1478619.07      6776251.16
      1479014.75      6776373.29
#Sta/Elev= 30
  4491.1 2427.62  4617.5 2422.87  4740.2 2415.81  4760.6 2413.40  4781.1 2409.13
  4801.5 2406.95  4852.7 2402.27  4861.6 2402.13  4922.9 2397.68  4944.7 2396.83
  4960.5 2395.29  5006.8 2394.47  5007.1 2393.97  5010.6 2393.97  5010.8 2394.47
  5041.5 2394.83  5074.1 2396.55  5100.4 2401.24  5106.8 2403.41  5112.0 2403.77
  5131.8 2408.43  5139.4 2411.26  5144.7 2411.18  5163.2 2416.28  5200.8 2419.80
  5226.0 2421.90  5257.4 2423.03  5275.3 2424.56  5280.5 2424.24  5414.1 2430.68
#Mann=5,-1,0
  4491.1    0.07       0  4922.9    0.16       0  5006.8    0.07       0
  5010.8    0.16       0  5200.8    0.07       0
Bank Sta=5006.8,5010.8
Exp/Cntr=0.3,0.1

Type RM Length L Ch R = 1,9386,487,487,487
BEGIN DESCRIPTION:
elmc128
END DESCRIPTION:
XS GIS Cut Line= 3
      1478158.55      6776602.61      1478557.51      6776694.04
      1478980.86      6776880.75
#Sta/Elev= 30
  4590.7 2422.19  4669.1 2417.49  4683.2 2415.87  4720.4 2408.90  4726.2 2406.99
  4751.2 2403.90  4823.0 2398.25  4871.8 2396.46  4950.9 2392.41  4993.8 2388.08
  5021.4 2387.95  5021.6 2387.45  5025.4 2387.95  5046.7 2389.82  5098.8 2390.58
  5174.2 2398.56  5192.1 2398.60  5197.6 2400.22  5215.4 2401.63  5226.8 2404.17
  5237.7 2405.20  5249.7 2408.97  5259.6 2409.82  5267.5 2411.93  5273.0 2414.49
  5281.4 2414.79  5296.3 2417.45  5325.1 2420.13  5425.0 2425.15  5462.7 2426.75
#Mann=5,-1,0
  4590.7    0.07       0  4871.8    0.16       0  5021.4    0.07       0
  5025.4    0.16       0  5425.0    0.07       0
Bank Sta=5021.4,5025.4
Exp/Cntr=0.3,0.1

Type RM Length L Ch R = 1,8899,447,447,447
BEGIN DESCRIPTION:
elmc127
END DESCRIPTION:
XS GIS Cut Line= 3
      1477982.20      6776927.57      1478410.74      6777135.67
      1478881.31      6777076.27
#Sta/Elev= 30
  4523.6 2421.32  4579.3 2419.76  4584.8 2418.97  4601.8 2419.11  4630.0 2416.89
  4669.5 2415.48  4682.4 2413.22  4692.1 2412.73  4698.8 2410.76  4749.1 2401.89
  4782.3 2398.25  4878.2 2390.45  4920.0 2388.83  4996.5 2382.87  4999.6 2381.71
  5012.4 2381.41  5012.6 2380.91  5016.4 2381.41  5020.4 2382.42  5054.7 2384.57
  5120.8 2386.48  5175.6 2388.45  5260.0 2397.78  5296.6 2403.43  5326.8 2409.18
  5347.0 2414.19  5367.2 2416.96  5407.5 2420.34  5456.4 2422.50  5474.3 2423.49
#Mann=8,-1,0
  4523.6    0.16       0  4698.8    0.07       0  4920.0    0.16       0
  5012.4    0.07       0  5016.4    0.16       0  5120.8    0.07       0
  5260.0    0.16       0  5456.4    0.07       0
Bank Sta=5012.4,5016.4
Exp/Cntr=0.3,0.1

Type RM Length L Ch R = 1,8452,427,427,427
BEGIN DESCRIPTION:
elmc126
END DESCRIPTION:
XS GIS Cut Line= 3
      1478028.54      6777509.34      1478458.58      6777539.65
      1478888.87      6777484.59
#Sta/Elev= 30
  4568.9 2416.86  4575.4 2416.26  4585.4 2413.94  4605.4 2411.83  4620.7 2408.25
  4625.7 2408.10  4655.6 2403.48  4685.6 2400.27  4701.4 2399.35  4755.8 2396.50
  4850.1 2387.00  4896.2 2384.05  4926.2 2382.98  4949.1 2380.35  4976.4 2376.60
  4984.4 2376.45  4984.6 2375.95  4988.4 2376.45  5016.6 2378.49  5048.7 2378.87
  5087.1 2379.93  5167.8 2384.84  5198.0 2388.43  5206.5 2390.42  5211.6 2390.40
  5291.3 2398.90  5349.2 2408.97  5366.0 2413.36  5402.2 2419.72  5433.8 2422.30
#Mann=8,-1,0
  4568.9    0.16       0  4701.4    0.07       0  4850.1    0.16       0
  4949.1    0.07       0  4984.4    0.07       0  4988.4    0.07       0
  5048.7    0.16       0  5402.2    0.07       0
Bank Sta=4984.4,4988.4
Exp/Cntr=0.3,0.1

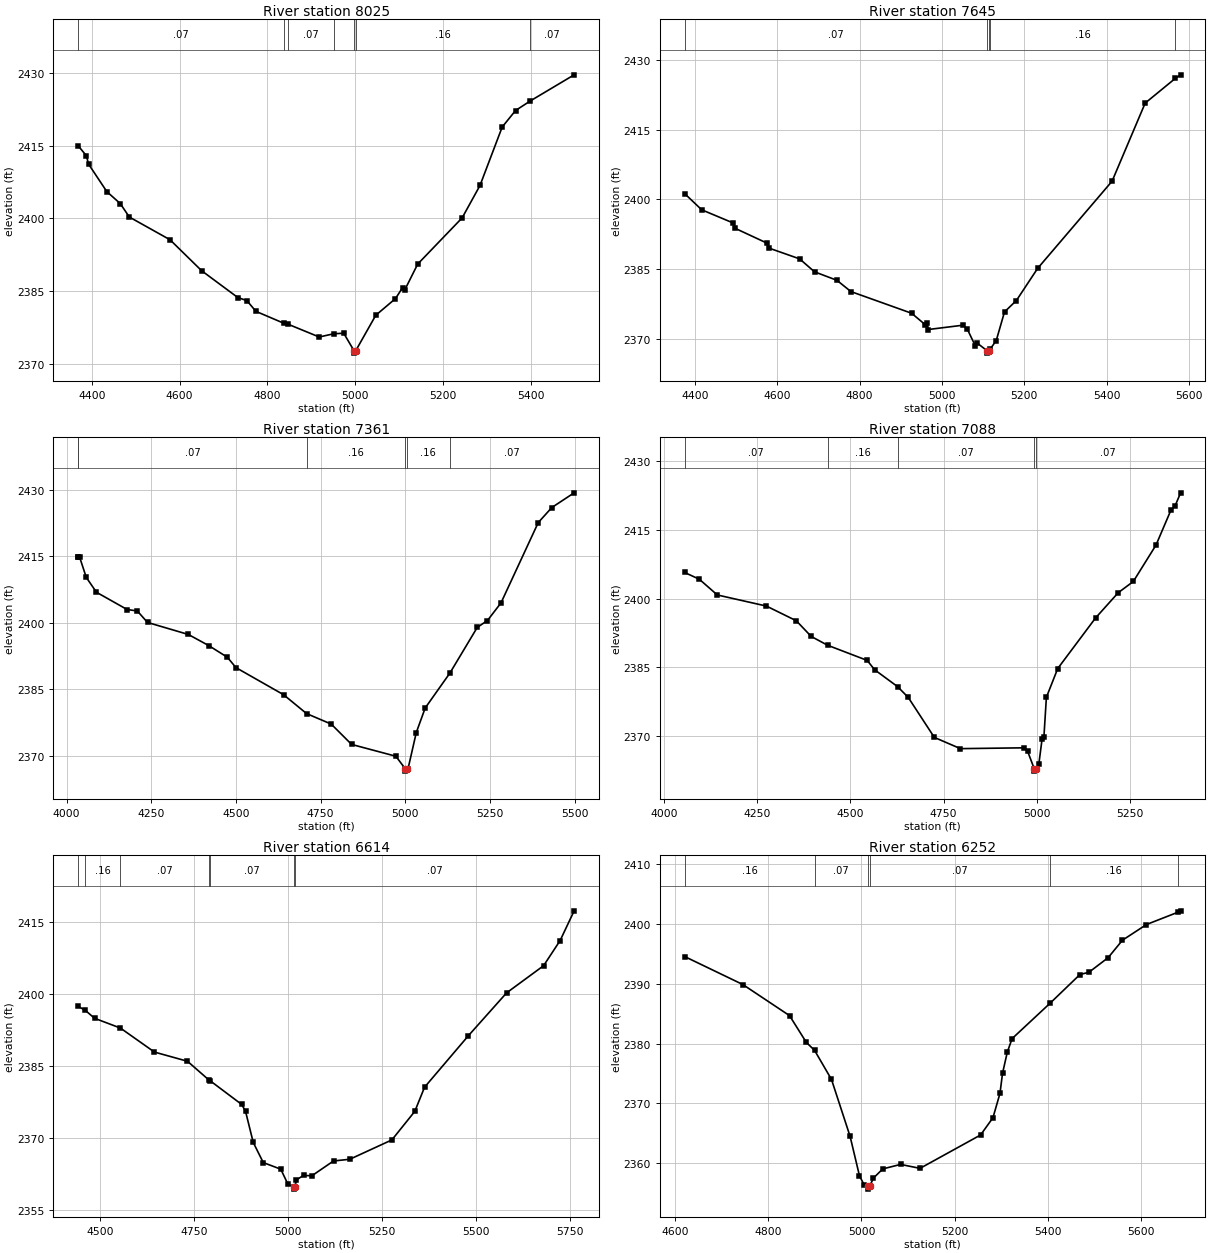
Type RM Length L Ch R = 1,8025,380,380,380
BEGIN DESCRIPTION:
elmc125
END DESCRIPTION:
XS GIS Cut Line= 3
      1477941.95      6777778.58      1478557.76      6777930.21
      1479046.68      6777849.76
#Sta/Elev= 30
  4369.1 2414.95  4387.6 2412.89  4392.8 2411.15  4434.3 2405.51  4464.9 2403.04
  4485.5 2400.28  4578.2 2395.60  4650.3 2389.22  4732.7 2383.70  4753.3 2383.07
  4773.9 2380.86  4838.5 2378.37  4847.7 2378.19  4918.1 2375.58  4951.0 2376.24
  4973.9 2376.36  4997.3 2372.76  4997.6 2372.26  5001.3 2372.76  5046.9 2380.05
  5091.7 2383.48  5108.1 2385.75  5113.2 2385.31  5142.4 2390.59  5243.7 2400.11
  5284.3 2406.77  5334.9 2418.81  5365.3 2422.20  5399.0 2424.18  5498.8 2429.55
#Mann=7,-1,0
  4369.1    0.07       0  4838.5    0.16       0  4847.7    0.07       0
  4951.0    0.16       0  4997.3    0.07       0  5001.3    0.16       0
  5399.0    0.07       0
Bank Sta=4997.3,5001.3
Exp/Cntr=0.3,0.1

Type RM Length L Ch R = 1,7645,284,284,284
BEGIN DESCRIPTION:
elmc124
END DESCRIPTION:
XS GIS Cut Line= 3
      1477898.59      6777936.40      1478421.60      6778214.92
      1479030.62      6778153.09
#Sta/Elev= 30
  4374.9 2401.23  4416.2 2397.76  4492.6 2394.93  4498.2 2393.75  4574.8 2390.60
  4580.4 2389.51  4654.1 2387.22  4690.3 2384.44  4744.7 2382.62  4778.7 2380.20
  4926.2 2375.54  4958.8 2373.12  4964.5 2373.54  4966.5 2372.05  5051.3 2372.98
  5061.3 2372.16  5080.9 2368.53  5086.0 2369.10  5109.6 2367.48  5109.8 2366.98
  5113.6 2367.48  5116.6 2367.80  5131.7 2369.67  5151.8 2375.83  5180.7 2378.28
  5232.2 2385.17  5413.1 2403.90  5493.5 2420.67  5566.5 2425.96  5579.6 2426.74
#Mann=5,-1,0
  4374.9    0.07       0  5109.6    0.07       0  5113.6    0.07       0
  5116.6    0.16       0  5566.5    0.07       0
Bank Sta=5109.6,5113.6
Exp/Cntr=0.3,0.1

Type RM Length L Ch R = 1,7361,273,273,273
BEGIN DESCRIPTION:
elmc264
END DESCRIPTION:
XS GIS Cut Line= 3
      1477691.31      6778484.15      1478712.49      6778388.22
      1479151.00      6778391.31
#Sta/Elev= 30
  4034.5 2414.76  4034.7 2414.76  4038.8 2414.76  4058.3 2410.23  4088.4 2406.88
  4178.8 2402.99  4209.0 2402.66  4239.1 2400.07  4359.6 2397.36  4419.9 2394.85
  4474.8 2392.22  4500.2 2389.88  4640.8 2383.77  4708.7 2379.51  4781.5 2377.14
  4841.7 2372.55  4972.3 2369.89  5000.4 2367.03  5000.7 2366.53  5004.4 2367.03
  5008.3 2367.07  5032.6 2375.23  5058.9 2380.77  5132.2 2388.69  5212.7 2398.96
  5242.7 2400.50  5282.7 2404.48  5392.7 2422.60  5432.7 2425.99  5498.7 2429.31
#Mann=6,-1,0
  4034.5    0.16       0  4034.7    0.07       0  4708.7    0.16       0
  5000.4    0.07       0  5004.4    0.16       0  5132.2    0.07       0
Bank Sta=5000.4,5004.4
Exp/Cntr=0.3,0.1

Type RM Length L Ch R = 1,7088,474,474,474
BEGIN DESCRIPTION:
elmc123
END DESCRIPTION:
XS GIS Cut Line= 3
      1477805.76      6778632.70      1478749.65      6778635.83
      1479130.15      6778573.92
#Sta/Elev= 30
  4056.1 2405.69  4095.3 2404.22  4143.6 2400.79  4275.3 2398.37  4355.3 2395.17
  4395.3 2391.75  4439.0 2389.84  4545.3 2386.53  4565.3 2384.49  4627.0 2380.80
  4655.3 2378.47  4725.3 2369.75  4795.3 2367.30  4965.3 2367.48  4975.3 2366.74
  4993.2 2362.90  4993.4 2362.40  4997.2 2362.90  5005.4 2363.89  5014.0 2369.32
  5019.1 2369.92  5025.7 2378.49  5056.1 2384.76  5157.4 2395.77  5218.2 2401.28
  5258.7 2403.73  5319.5 2411.66  5360.0 2419.37  5370.2 2420.12  5385.5 2423.05
#Mann=5,-1,0
  4056.1    0.07       0  4439.0    0.16       0  4627.0    0.07       0
  4993.2    0.07       0  4997.2    0.07       0
Bank Sta=4993.2,4997.2
Exp/Cntr=0.3,0.1

Type RM Length L Ch R = 1,6614,362,362,362
BEGIN DESCRIPTION:
elmc122
END DESCRIPTION:
XS GIS Cut Line= 3
      1477932.66      6778784.34      1478594.90      6778948.35
      1479221.60      6778827.95
#Sta/Elev= 30
  4441.5 2397.39  4459.5 2396.64  4485.1 2394.93  4553.9 2392.90  4644.4 2387.91
  4732.4 2386.00  4790.0 2382.07  4793.2 2381.92  4876.6 2377.03  4886.9 2375.62
  4907.5 2369.12  4934.2 2364.94  4980.7 2363.57  5000.2 2360.40  5015.0 2359.92
  5015.2 2359.42  5019.0 2359.92  5022.1 2361.33  5041.4 2362.27  5063.5 2362.19
  5121.2 2365.27  5164.6 2365.63  5276.6 2369.65  5337.7 2375.59  5363.6 2380.60
  5480.2 2391.30  5582.1 2400.22  5680.5 2405.86  5724.6 2411.10  5761.9 2417.27
#Mann=7,-1,0
  4441.5    0.07       0  4459.5    0.16       0  4553.9    0.07       0
  4790.0    0.16       0  4793.2    0.07       0  5015.0    0.07       0
  5019.0    0.07       0
Bank Sta=5015,5019
Exp/Cntr=0.3,0.1

Type RM Length L Ch R = 1,6252,560,560,560
BEGIN DESCRIPTION:
elmc121
END DESCRIPTION:
XS GIS Cut Line= 3
      1478180.18      6779223.77      1478619.66      6779239.25
      1479226.18      6779090.71
#Sta/Elev= 30
  4620.7 2394.54  4745.6 2389.86  4845.7 2384.67  4881.8 2380.19  4899.4 2378.87
  4935.7 2374.01  4975.7 2364.48  4995.8 2357.90  5005.8 2356.40  5013.8 2356.18
  5014.0 2355.68  5017.8 2356.18  5025.8 2357.53  5045.8 2359.06  5084.1 2359.81
  5125.7 2359.15  5255.7 2364.73  5282.2 2367.61  5297.3 2371.69  5302.7 2375.01
  5313.0 2378.58  5323.3 2380.83  5404.5 2386.72  5468.9 2391.54  5488.1 2391.91
  5529.3 2394.35  5560.1 2397.27  5611.6 2399.89  5678.6 2401.93  5684.9 2402.18
#Mann=6,-1,0
  4620.7    0.16       0  4899.4    0.07       0  5013.8    0.07       0
  5017.8    0.07       0  5404.5    0.16       0  5678.6    0.07       0
Bank Sta=5013.8,5017.8
Exp/Cntr=0.3,0.1

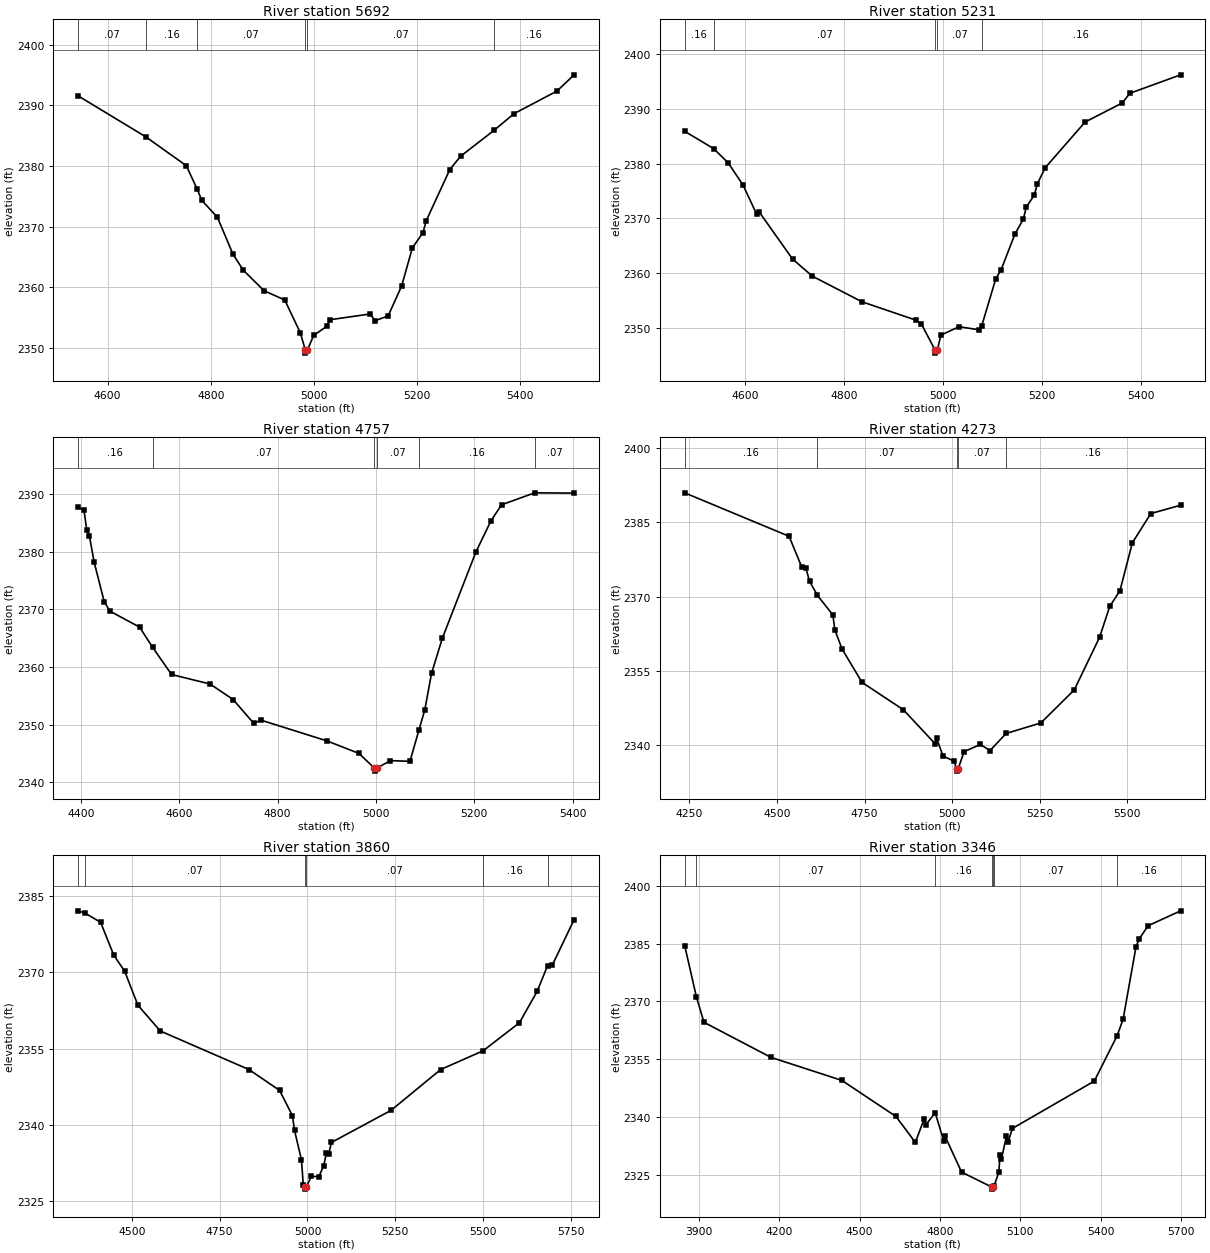
Type RM Length L Ch R = 1,5692,461,461,461
BEGIN DESCRIPTION:
elmc120
END DESCRIPTION:
XS GIS Cut Line= 3
      1478316.37      6779663.22      1478771.25      6779621.34
      1479257.17      6779486.82
#Sta/Elev= 30
  4543.2 2391.54  4674.2 2384.80  4752.7 2380.05  4773.9 2376.15  4782.8 2374.33
  4813.0 2371.54  4843.1 2365.47  4863.2 2362.83  4903.3 2359.47  4943.5 2357.93
  4973.6 2352.53  4983.3 2349.69  4983.6 2349.19  4987.3 2349.69  4999.4 2352.11
  5024.6 2353.58  5030.5 2354.68  5109.5 2355.64  5118.0 2354.51  5143.8 2355.32
  5169.9 2360.24  5190.7 2366.52  5211.4 2369.04  5217.6 2371.00  5263.3 2379.42
  5284.1 2381.60  5349.5 2385.91  5387.8 2388.62  5470.8 2392.33  5504.2 2395.01
#Mann=6,-1,0
  4543.2    0.07       0  4674.2    0.16       0  4773.9    0.07       0
  4983.3    0.07       0  4987.3    0.07       0  5349.5    0.16       0
Bank Sta=4983.3,4987.3
Exp/Cntr=0.3,0.1

Type RM Length L Ch R = 1,5231,474,474,474
BEGIN DESCRIPTION:
elmc119
END DESCRIPTION:
XS GIS Cut Line= 3
      1478477.27      6780009.82      1478998.92      6779985.80
      1479431.77      6779778.57
#Sta/Elev= 30
  4477.8 2385.88  4536.3 2382.72  4565.6 2380.13  4595.7 2376.07  4623.4 2370.71
  4628.4 2371.15  4695.8 2362.55  4735.8 2359.43  4835.9 2354.76  4946.0 2351.37
  4956.0 2350.71  4984.1 2345.88  4984.3 2345.38  4988.1 2345.88  4995.5 2348.67
  5032.1 2350.20  5071.8 2349.65  5078.2 2350.41  5106.5 2358.99  5117.2 2360.60
  5145.4 2367.19  5162.0 2369.81  5168.0 2372.04  5184.1 2374.22  5190.7 2376.34
  5206.3 2379.23  5286.9 2387.57  5361.5 2391.03  5377.6 2392.83  5479.9 2396.19
#Mann=5,-1,0
  4477.8    0.16       0  4536.3    0.07       0  4984.1    0.07       0
  4988.1    0.07       0  5078.2    0.16       0
Bank Sta=4984.1,4988.1
Exp/Cntr=0.3,0.1

Type RM Length L Ch R = 1,4757,484,484,484
BEGIN DESCRIPTION:
elmc118
END DESCRIPTION:
XS GIS Cut Line= 3
      1478653.73      6780517.33      1479241.80      6780374.36
      1479609.97      6780210.96
#Sta/Elev= 30
  4394.8 2387.68  4406.4 2387.26  4412.3 2383.70  4417.5 2382.78  4427.0 2378.25
  4447.6 2371.36  4459.2 2369.70  4519.6 2366.93  4545.8 2363.46  4584.5 2358.72
  4662.8 2357.07  4709.7 2354.38  4751.5 2350.26  4766.6 2350.80  4900.4 2347.21
  4965.4 2345.04  4997.0 2342.47  4997.3 2341.97  5001.1 2342.47  5029.4 2343.79
  5069.1 2343.67  5087.2 2349.06  5099.2 2352.57  5112.9 2358.90  5134.8 2364.99
  5203.2 2379.97  5233.3 2385.29  5255.2 2388.13  5322.5 2390.21  5402.8 2390.16
#Mann=6,-1,0
  4394.8    0.16       0  4545.8    0.07       0  4997.0    0.07       0
  5001.1    0.07       0  5087.2    0.16       0  5322.5    0.07       0
Bank Sta=4997,5001.1
Exp/Cntr=0.3,0.1

Type RM Length L Ch R = 1,4273,413,413,413
BEGIN DESCRIPTION:
elmc117
END DESCRIPTION:
XS GIS Cut Line= 3
      1478458.74      6780913.45      1479368.56      6780690.64
      1479613.02      6780279.07
#Sta/Elev= 30
  4236.4 2390.98  4534.4 2382.19  4570.9 2375.90  4582.6 2375.68  4592.9 2373.07
  4615.4 2370.22  4659.3 2366.29  4665.0 2363.24  4685.6 2359.39  4742.5 2352.64
  4860.6 2347.10  4950.5 2340.27  4955.7 2341.29  4973.8 2337.72  5004.7 2336.74
  5013.0 2335.19  5013.2 2334.69  5017.1 2335.19  5033.8 2338.63  5080.5 2340.09
  5107.7 2338.84  5153.8 2342.31  5253.0 2344.44  5348.5 2351.14  5420.4 2361.75
  5449.8 2368.05  5478.6 2371.17  5514.1 2380.88  5566.7 2386.79  5651.8 2388.47
#Mann=5,-1,0
  4236.4    0.16       0  4615.4    0.07       0  5013.0    0.07       0
  5017.1    0.07       0  5153.8    0.16       0
Bank Sta=5013,5017.1
Exp/Cntr=0.3,0.1

Type RM Length L Ch R = 1,3860,514,514,514
BEGIN DESCRIPTION:
elmc116
END DESCRIPTION:
XS GIS Cut Line= 4
      1478724.85      6781256.96      1479339.80      6781038.49
      1479622.32      6780733.96      1479668.74      6780393.51
#Sta/Elev= 30
  4347.4 2382.07  4367.6 2381.59  4411.2 2379.81  4448.6 2373.35  4479.5 2370.22
  4517.4 2363.51  4581.0 2358.45  4833.8 2350.86  4920.6 2346.77  4957.2 2341.80
  4963.1 2338.91  4982.8 2333.13  4988.1 2328.12  4992.8 2327.87  4993.0 2327.37
  4996.9 2327.87  5011.2 2329.90  5032.2 2329.80  5046.4 2332.01  5053.8 2334.49
  5060.6 2334.24  5067.9 2336.54  5237.5 2342.84  5379.2 2350.88  5499.6 2354.55
  5603.1 2360.06  5653.5 2366.22  5683.4 2371.31  5696.6 2371.37  5759.0 2380.35
#Mann=6,-1,0
  4347.4    0.16       0  4367.6    0.07       0  4992.8    0.07       0
  4996.9    0.07       0  5499.6    0.16       0  5683.4    0.07       0
Bank Sta=4992.8,4996.9
Exp/Cntr=0.3,0.1

Type RM Length L Ch R = 1,3346,442,442,442
BEGIN DESCRIPTION:
elmc115
END DESCRIPTION:
XS GIS Cut Line= 3
      1478721.74      6781433.36      1479848.23      6781105.32
      1480477.79      6780852.26
#Sta/Elev= 30
  3847.1 2384.53  3890.6 2371.27  3919.1 2364.59  4169.2 2355.49  4433.8 2349.51
  4636.1 2340.14  4708.3 2333.41  4741.8 2339.57  4747.0 2337.90  4782.5 2341.13
  4814.0 2333.86  4819.2 2335.02  4881.0 2325.70  4994.8 2321.77  4995.1 2321.27
  4999.6 2321.77  5001.9 2322.01  5020.4 2325.72  5024.4 2330.25  5029.8 2329.05
  5048.6 2335.08  5054.0 2333.38  5070.8 2337.03  5376.6 2349.32  5461.3 2361.03
  5484.1 2365.37  5532.4 2384.24  5545.0 2386.32  5577.3 2389.66  5698.9 2393.54
#Mann=7,-1,0
  3847.1    0.16       0  3890.6    0.07       0  4782.5    0.16       0
  4994.8    0.07       0  4999.6    0.16       0  5001.9    0.07       0
  5461.3    0.16       0
Bank Sta=4994.8,4999.6
Exp/Cntr=0.3,0.1

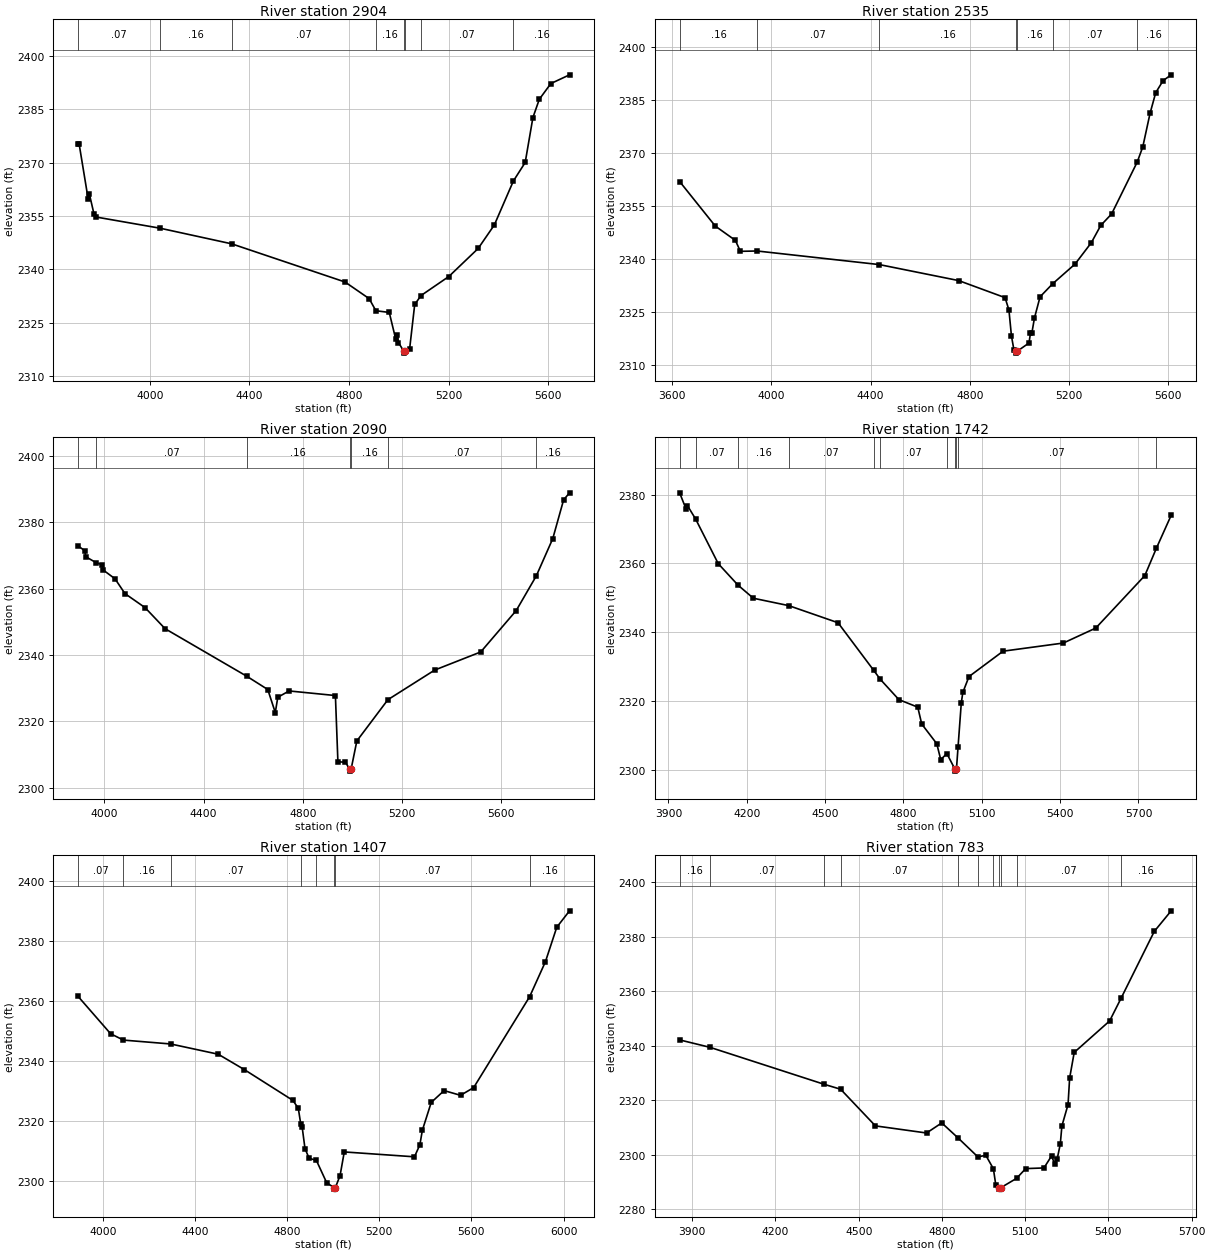
Type RM Length L Ch R = 1,2904,369,369,369
BEGIN DESCRIPTION:
elmc114
END DESCRIPTION:
XS GIS Cut Line= 3
      1478731.08      6781557.14      1480013.47      6781431.81
      1480677.58      6781263.15
#Sta/Elev= 30
  3711.5 2375.31  3716.0 2375.31  3752.3 2359.80  3757.3 2361.16  3775.7 2355.57
  3785.8 2354.69  4041.2 2351.56  4328.7 2347.16  4783.8 2336.41  4880.5 2331.73
  4907.6 2328.32  4961.3 2327.84  4987.1 2320.35  4992.2 2321.57  4998.3 2319.37
  5019.8 2316.88  5020.1 2316.38  5024.7 2316.88  5042.9 2317.46  5063.5 2330.09
  5089.1 2332.61  5200.5 2337.96  5318.2 2345.85  5383.3 2352.49  5459.7 2364.86
  5507.1 2370.07  5538.1 2382.72  5563.9 2387.89  5610.3 2392.31  5685.2 2394.76
#Mann=8,-1,0
  3711.5    0.07       0  4041.2    0.16       0  4328.7    0.07       0
  4907.6    0.16       0  5019.8    0.07       0  5024.7    0.16       0
  5089.1    0.07       0  5459.7    0.16       0
Bank Sta=5019.8,5024.7
Exp/Cntr=0.3,0.1

Type RM Length L Ch R = 1,2535,445,445,445
BEGIN DESCRIPTION:
elmc263
END DESCRIPTION:
XS GIS Cut Line= 3
      1478792.92      6781940.88      1480191.73      6781727.34
      1480689.93      6781458.13
#Sta/Elev= 30
  3630.4 2361.98  3774.1 2349.38  3855.1 2345.33  3875.3 2342.24  3943.0 2342.33
  4435.2 2338.49  4755.4 2333.96  4942.1 2329.14  4957.7 2325.65  4967.8 2318.32
  4977.9 2314.34  4985.6 2313.95  4985.9 2313.45  4990.5 2313.95  5038.6 2316.32
  5044.5 2319.09  5050.0 2319.09  5060.5 2323.35  5083.2 2329.38  5134.0 2333.07
  5224.1 2338.63  5289.7 2344.67  5327.8 2349.56  5371.6 2352.81  5474.8 2367.49
  5497.2 2371.77  5526.5 2381.26  5549.3 2387.09  5579.1 2390.51  5611.7 2392.15
#Mann=7,-1,0
  3630.4    0.16       0  3943.0    0.07       0  4435.2    0.16       0
  4985.6    0.07       0  4990.5    0.16       0  5134.0    0.07       0
  5474.8    0.16       0
Bank Sta=4985.6,4990.5
Exp/Cntr=0.3,0.1

Type RM Length L Ch R = 1,2090,348,348,348
BEGIN DESCRIPTION:
elmc262
END DESCRIPTION:
XS GIS Cut Line= 3
      1478907.41      6782287.48      1480185.55      6782098.70
      1480827.80      6781842.42
#Sta/Elev= 30
  3893.1 2372.88  3919.8 2371.43  3924.9 2369.58  3967.7 2367.73  3989.4 2367.23
  3994.5 2365.60  4042.3 2362.95  4082.7 2358.47  4163.6 2354.25  4244.5 2347.89
  4573.5 2333.58  4658.9 2329.55  4689.2 2322.60  4699.3 2327.21  4744.9 2329.12
  4931.8 2327.73  4941.9 2307.75  4972.3 2307.63  4990.0 2305.44  4990.4 2304.94
  4994.9 2305.44  5018.3 2314.04  5143.6 2326.48  5332.6 2335.42  5518.3 2340.88
  5661.4 2353.36  5742.5 2363.82  5809.0 2375.07  5852.7 2386.75  5876.6 2388.86
#Mann=7,-1,0
  3893.1    0.16       0  3967.7    0.07       0  4573.5    0.16       0
  4990.0    0.07       0  4994.9    0.16       0  5143.6    0.07       0
  5742.5    0.16       0
Bank Sta=4990,4994.9
Exp/Cntr=0.3,0.1

Type RM Length L Ch R = 1,1742,335,335,335
BEGIN DESCRIPTION:
elmc261
END DESCRIPTION:
XS GIS Cut Line= 3
      1479096.27      6782637.16      1479950.35      6782497.91
      1480807.53      6781950.18
#Sta/Elev= 30
  3942.7 2380.54  3967.7 2375.74  3972.7 2376.80  4004.1 2372.89  4090.6 2359.92
  4166.7 2353.64  4225.1 2349.86  4360.6 2347.71  4549.3 2342.73  4685.7 2328.90
  4711.3 2326.26  4782.4 2320.35  4854.7 2318.16  4869.9 2313.25  4927.5 2307.52
  4942.7 2302.89  4966.1 2304.65  4997.6 2300.04  4998.0 2299.54  5002.8 2300.04
  5009.1 2306.67  5021.4 2319.38  5027.3 2322.44  5050.9 2327.06  5181.5 2334.45
  5412.2 2336.82  5536.5 2341.18  5724.3 2356.45  5768.7 2364.43  5825.3 2374.01
#Mann=11,-1,0
  3942.7    0.16       0  4004.1    0.07       0  4166.7    0.16       0
  4360.6    0.07       0  4685.7    0.16       0  4711.3    0.07       0
  4966.1    0.16       0  4997.6    0.07       0  5002.8    0.16       0
  5009.1    0.07       0  5768.7    0.16       0
Bank Sta=4997.6,5002.8
Exp/Cntr=0.3,0.1

Type RM Length L Ch R = 1,1407,624,624,624
BEGIN DESCRIPTION:
elmc260
END DESCRIPTION:
XS GIS Cut Line= 4
      1479145.72      6782730.00      1479817.28      6782850.70
      1480569.28      6782528.86      1481048.98      6782114.15
#Sta/Elev= 30
  3891.8 2361.54  4033.3 2349.10  4088.9 2346.98  4294.1 2345.69  4500.7 2342.28
  4614.4 2337.15  4824.8 2326.93  4848.4 2324.30  4859.1 2319.04  4865.3 2317.97
  4877.5 2310.86  4895.6 2307.66  4926.8 2306.98  4971.8 2299.51  5004.1 2297.91
  5004.5 2297.41  5009.3 2297.91  5029.8 2301.93  5048.0 2309.78  5352.8 2308.16
  5376.3 2312.16  5387.0 2316.96  5425.6 2326.25  5481.5 2330.18  5552.8 2328.61
  5609.8 2331.17  5852.9 2361.41  5921.4 2373.03  5970.7 2384.51  6026.2 2389.97
#Mann=8,-1,0
  3891.8    0.07       0  4088.9    0.16       0  4294.1    0.07       0
  4859.1    0.16       0  4926.8    0.07       0  5004.1    0.07       0
  5009.3    0.07       0  5852.9    0.16       0
Bank Sta=5004.1,5009.3
Exp/Cntr=0.3,0.1

Type RM Length L Ch R = 1,783,596,596,596
BEGIN DESCRIPTION:
elmc259
END DESCRIPTION:
XS GIS Cut Line= 4
      1479721.31      6782977.58      1480655.93      6782909.50
      1480888.03      6782565.99      1481079.53      6782192.26
#Sta/Elev= 30
  3854.6 2342.15  3964.3 2339.42  4375.6 2325.86  4434.9 2324.05  4560.2 2310.61
  4744.6 2308.00  4799.3 2311.70  4859.4 2306.06  4929.4 2299.24  4958.1 2299.81
  4985.4 2294.88  4994.0 2289.00  5006.4 2287.91  5006.8 2287.41  5011.7 2287.91
  5068.9 2291.36  5101.9 2294.94  5167.6 2295.18  5194.9 2299.55  5206.3 2296.73
  5215.7 2298.64  5226.5 2303.95  5232.3 2310.58  5254.5 2318.44  5260.2 2328.15
  5276.7 2337.56  5404.3 2349.10  5446.6 2357.64  5565.3 2381.96  5626.2 2389.50
#Mann=11,-1,0
  3854.6    0.16       0  3964.3    0.07       0  4375.6    0.16       0
  4434.9    0.07       0  4859.4    0.16       0  4929.4    0.07       0
  4985.4    0.16       0  5006.4    0.07       0  5011.7    0.16       0
  5068.9    0.07       0  5446.6    0.16       0
Bank Sta=5006.4,5011.7
Exp/Cntr=0.3,0.1

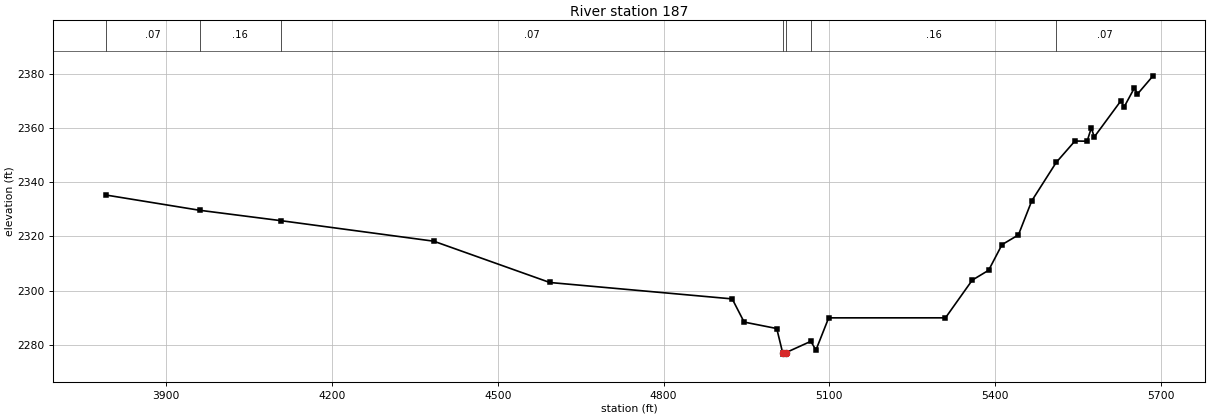
Type RM Length L Ch R = 1,187,0,0,0
BEGIN DESCRIPTION:
elmc258
END DESCRIPTION:
XS GIS Cut Line= 4
      1479971.97      6783008.53      1481018.00      6782968.30
      1481293.43      6782810.47      1481490.73      6782317.21
#Sta/Elev= 30
  3790.5 2335.26  3960.4 2329.62  4106.9 2325.80  4384.0 2318.21  4594.1 2302.96
  4924.3 2296.90  4945.9 2288.34  5004.9 2285.96  5015.6 2277.01  5016.0 2276.51
  5020.9 2277.01  5066.5 2281.23  5075.9 2278.04  5098.9 2289.90  5310.3 2289.91
  5358.8 2303.84  5388.4 2307.47  5412.6 2316.93  5442.3 2320.52  5466.5 2333.12
  5510.8 2347.30  5544.6 2355.19  5566.7 2355.12  5574.2 2360.02  5579.6 2356.68
  5628.0 2370.09  5633.4 2367.68  5652.3 2374.80  5657.7 2372.50  5686.0 2379.26
#Mann=7,-1,0
  3790.5    0.07       0  3960.4    0.16       0  4106.9    0.07       0
  5015.6    0.07       0  5020.9    0.07       0  5066.5    0.16       0
  5510.8    0.07       0
Bank Sta=5015.6,5020.9
Exp/Cntr=0.3,0.1

Chan Stop Cuts=-1