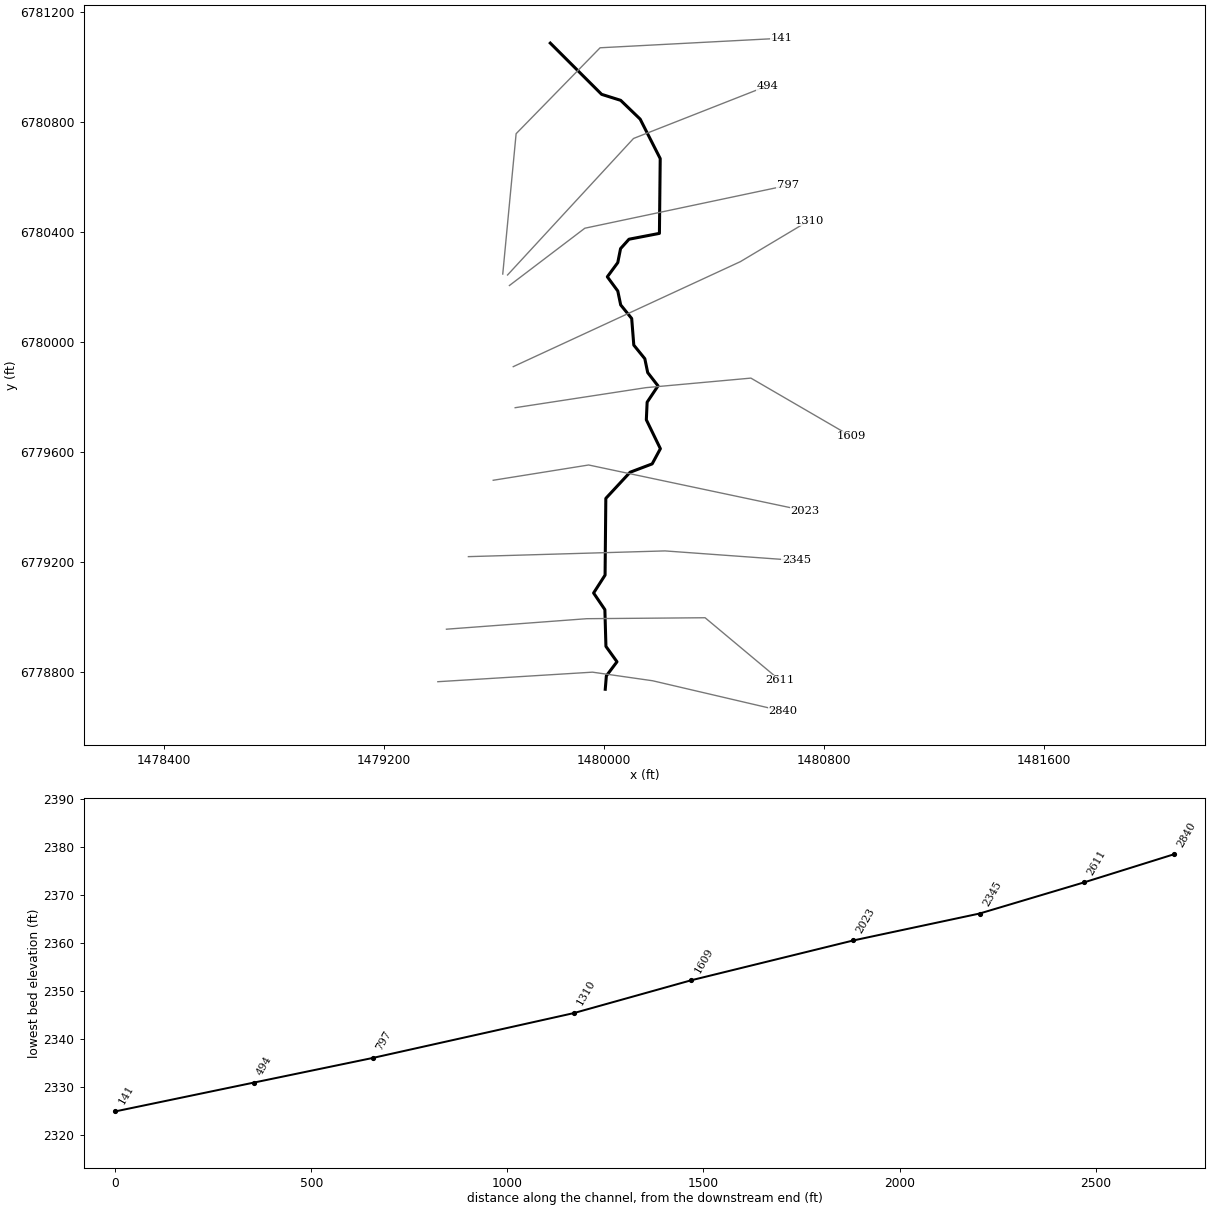
--- Elm 15.prj (project) ---

Proj Title=Elm 15 Base Level Engineering
Current Plan=p01
Default Exp/Contr=0.3,0.1
English Units
Geom File=g01
Flow File=f01
Plan File=p01
BEGIN DESCRIPTION:
Elm 15
END DESCRIPTION:

--- Elm 15.p01 (plan) ---

Plan Title=Multiple Run
Short Identifier=Multiple
Geom File=g01
Flow File=f01
Subcritical Flow
K Sum by GR= 0
Std Step Tol= 0.01
Critical Tol= 0.01
Num of Std Step Trials= 20
Max Error Tol= 0.3
Flow Tol Ratio= 0.001
Split Flow NTrial= 30
Split Flow Tol= 0.02
Split Flow Ratio= 0.02
Log Output Level= 0
Friction Slope Method= 1
Unsteady Friction Slope Method= 2
Unsteady Bridges Friction Slope Method= 1
Parabolic Critical Depth
Global Vel Dist=  1 , 1 , 1
Global Log Level= 0
CheckData=True
Encroach Param= -1, 0, 0, 0
BEGIN DESCRIPTION:
Multiple Run
END DESCRIPTION:

--- Elm 15.f01 (steady flow) ---

Flow Title=Multiple
Number of Profiles=7
Profile Names=10-year,25-year,50-year,1pct_min,100-year,1pct_plu,500-year
River Rch & RM= Elm 15,Reach-1,2840
     168     230     280     212     341     469     508
Boundary for River Rch & Prof#=Elm 15,Reach-1,1
Up Type=0
Dn Type=3
Dn Slope=0.005
Boundary for River Rch & Prof#=Elm 15,Reach-1,2
Up Type=0
Dn Type=3
Dn Slope=0.005
Boundary for River Rch & Prof#=Elm 15,Reach-1,3
Up Type=0
Dn Type=3
Dn Slope=0.005
Boundary for River Rch & Prof#=Elm 15,Reach-1,4
Up Type=0
Dn Type=3
Dn Slope=0.005
Boundary for River Rch & Prof#=Elm 15,Reach-1,5
Up Type=0
Dn Type=3
Dn Slope=0.005
Boundary for River Rch & Prof#=Elm 15,Reach-1,6
Up Type=0
Dn Type=3
Dn Slope=0.005
Boundary for River Rch & Prof#=Elm 15,Reach-1,7
Up Type=0
Dn Type=3
Dn Slope=0.005

--- Elm 15.g01 (geometry) ---

Geom Title=Existing Conditions

River Reach=Elm 15,Reach-1
Reach XY= 30
      1480005.00      6778738.00      1480009.00      6778786.64
      1480047.69      6778837.96      1480007.46      6778893.86
      1480003.61      6779027.56      1479962.56      6779088.00
      1480004.34      6779153.16      1480007.05      6779432.16
      1480095.32      6779527.22      1480175.68      6779557.63
      1480205.53      6779612.88      1480154.43      6779717.95
      1480157.37      6779782.11      1480196.95      6779841.32
      1480159.42      6779889.64      1480148.91      6779940.17
      1480108.83      6779989.58      1480101.17      6780086.42
      1480061.09      6780135.83      1480050.58      6780186.36
      1480012.50      6780238.00      1480050.53      6780289.68
      1480060.69      6780340.57      1480091.38      6780374.73
      1480202.06      6780395.97      1480204.94      6780667.97
      1480132.01      6780811.52      1480061.07      6780879.85
      1479991.79      6780901.63      1479805.00      6781088.00

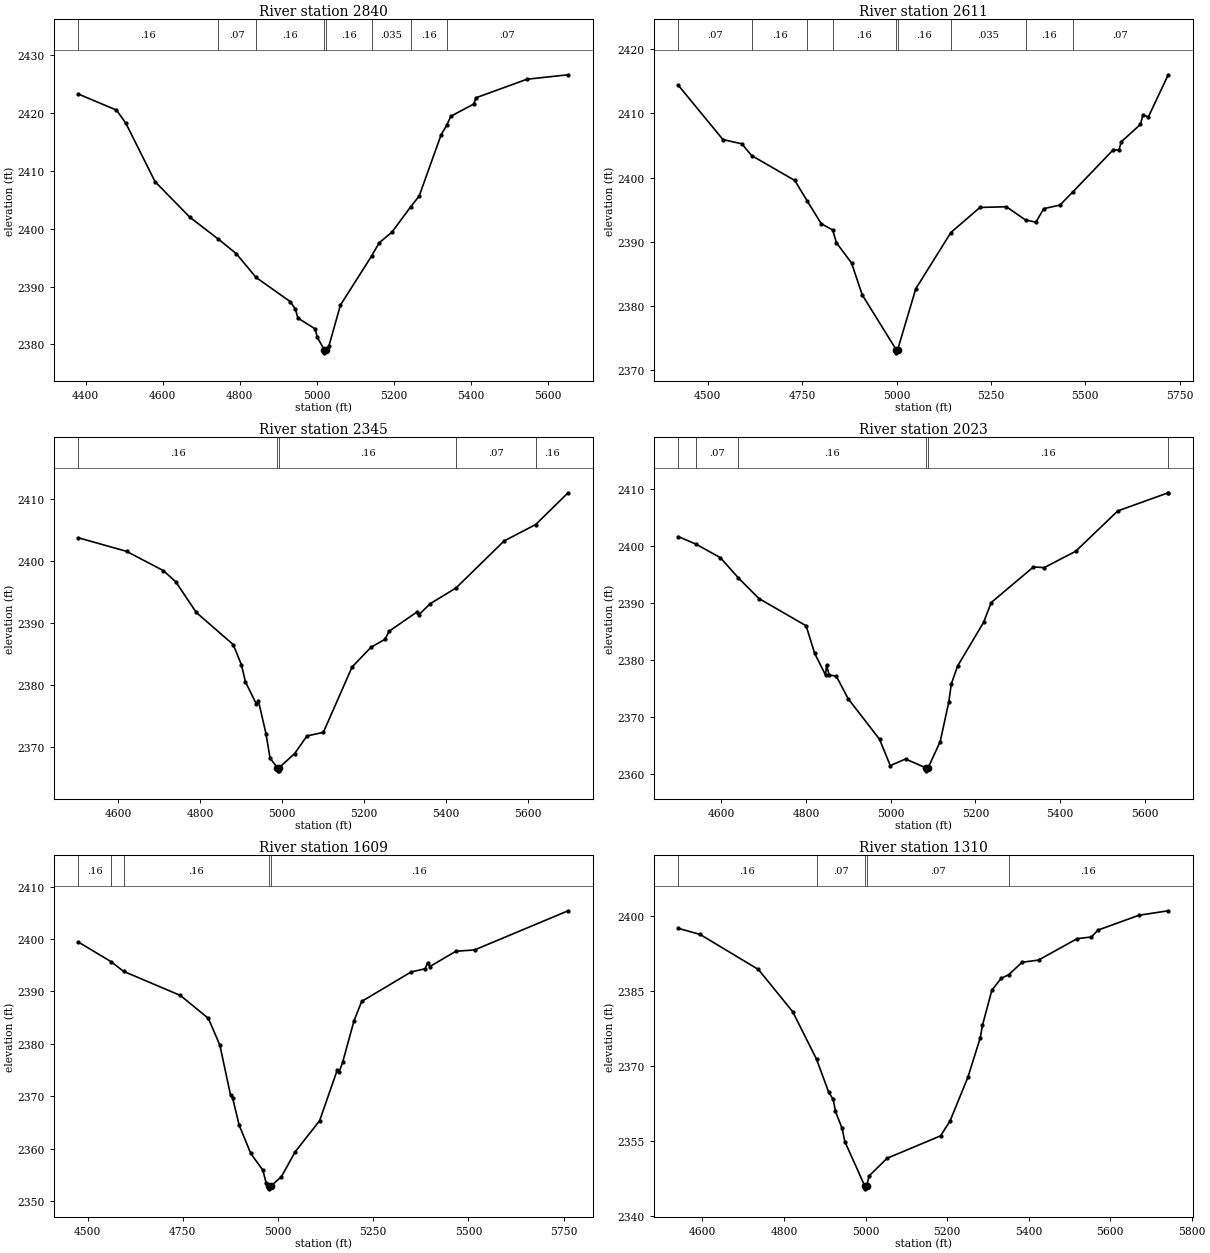
Type RM Length L Ch R = 1,2840,229,229,229
BEGIN DESCRIPTION:
elmc279
END DESCRIPTION:
XS GIS Cut Line= 4
      1479395.93      6778765.43      1479958.47      6778800.15
      1480177.22      6778768.90      1480651.47      6778658.13
#Sta/Elev= 30
  4380.5 2423.27  4479.8 2420.49  4504.1 2418.22  4580.0 2408.12  4670.4 2401.97
  4743.2 2398.25  4790.4 2395.71  4842.2 2391.57  4930.6 2387.41  4944.1 2386.12
  4950.7 2384.56  4995.4 2382.69  5001.2 2381.22  5019.4 2379.05  5019.7 2378.55
  5023.4 2379.05  5031.5 2379.80  5061.1 2386.80  5141.9 2395.26  5161.4 2397.54
  5194.9 2399.41  5243.8 2403.81  5265.5 2405.64  5322.5 2416.23  5336.8 2417.85
  5347.7 2419.43  5407.5 2421.54  5412.6 2422.61  5545.3 2425.82  5652.1 2426.59
#Mann=8,-1,0
  4380.5    0.16       0  4743.2    0.07       0  4842.2    0.16       0
  5019.4    0.07       0  5023.4    0.16       0  5141.9   0.035       0
  5243.8    0.16       0  5336.8    0.07       0
Bank Sta=5019.4,5023.4
Exp/Cntr=0.3,0.1

Type RM Length L Ch R = 1,2611,266,266,266
BEGIN DESCRIPTION:
elmc278
END DESCRIPTION:
XS GIS Cut Line= 4
      1479427.17      6778956.40      1479937.64      6778994.60
      1480368.19      6778998.07      1480641.27      6778769.93
#Sta/Elev= 30
  4421.8 2414.36  4540.0 2405.91  4590.1 2405.25  4616.1 2403.42  4730.5 2399.54
  4763.7 2396.31  4800.7 2392.80  4830.7 2391.84  4840.8 2389.84  4880.9 2386.69
  4909.1 2381.73  4999.1 2373.20  4999.3 2372.70  5003.1 2373.20  5051.1 2382.68
  5144.0 2391.43  5221.1 2395.34  5291.1 2395.45  5341.9 2393.39  5369.4 2393.05
  5390.2 2395.15  5433.2 2395.71  5466.5 2397.71  5575.0 2404.36  5589.3 2404.25
  5595.8 2405.57  5646.6 2408.28  5653.1 2409.78  5667.4 2409.43  5720.1 2416.00
#Mann=9,-1,0
  4421.8    0.07       0  4616.1    0.16       0  4763.7    0.07       0
  4830.7    0.16       0  4999.1    0.07       0  5003.1    0.16       0
  5144.0   0.035       0  5341.9    0.16       0  5466.5    0.07       0
Bank Sta=4999.1,5003.1
Exp/Cntr=0.3,0.1

Type RM Length L Ch R = 1,2345,322,322,322
BEGIN DESCRIPTION:
elmc277
END DESCRIPTION:
XS GIS Cut Line= 3
      1479507.11      6779220.29      1480222.36      6779241.13
      1480700.75      6779206.46
#Sta/Elev= 30
  4502.5 2403.74  4620.4 2401.55  4710.5 2398.44  4740.5 2396.64  4790.5 2391.72
  4880.6 2386.55  4900.6 2383.30  4910.6 2380.52  4937.3 2376.95  4942.3 2377.44
  4960.6 2372.19  4970.6 2368.25  4988.6 2366.72  4988.8 2366.22  4992.3 2366.22
  4992.6 2366.72  5030.6 2369.01  5060.6 2371.83  5100.6 2372.42  5170.7 2382.94
  5216.9 2386.12  5250.8 2387.38  5260.8 2388.68  5328.2 2391.76  5333.2 2391.31
  5361.1 2393.12  5424.1 2395.65  5541.5 2403.22  5618.4 2405.86  5697.7 2410.98
#Mann=5,-1,0
  4502.5    0.16       0  4988.6    0.07       0  4992.6    0.16       0
  5424.1    0.07       0  5618.4    0.16       0
Bank Sta=4988.6,4992.6
Exp/Cntr=0.3,0.1

Type RM Length L Ch R = 1,2023,414,414,414
BEGIN DESCRIPTION:
elmc276
END DESCRIPTION:
XS GIS Cut Line= 3
      1479597.37      6779498.07      1479944.58      6779553.63
      1480731.36      6779387.26
#Sta/Elev= 30
  4499.0 2401.62  4540.8 2400.29  4598.2 2397.93  4640.6 2394.39  4689.0 2390.78
  4800.4 2386.01  4820.7 2381.17  4846.3 2377.38  4848.6 2379.13  4854.9 2377.38
  4871.5 2377.20  4899.5 2373.26  4973.7 2366.13  4999.0 2361.53  5035.0 2362.68
  5084.1 2361.11  5084.4 2360.61  5088.1 2361.11  5116.8 2365.73  5137.2 2372.71
  5143.0 2375.81  5157.7 2378.94  5219.0 2386.58  5237.3 2390.08  5336.8 2396.30
  5362.1 2396.19  5436.2 2399.03  5535.9 2406.12  5654.1 2409.27  5654.8 2409.29
#Mann=6,-1,0
  4499.0    0.16       0  4540.8    0.07       0  4640.6    0.16       0
  5084.1    0.07       0  5088.1    0.16       0  5654.1    0.07       0
Bank Sta=5084.1,5088.1
Exp/Cntr=0.3,0.1

Type RM Length L Ch R = 1,1609,299,299,299
BEGIN DESCRIPTION:
elmc275
END DESCRIPTION:
XS GIS Cut Line= 4
      1479677.24      6779761.96      1480152.91      6779834.88
      1480534.86      6779869.60      1480899.45      6779657.79
#Sta/Elev= 30
  4475.2 2399.44  4561.1 2395.70  4594.3 2393.83  4743.5 2389.23  4817.0 2384.85
  4847.3 2379.70  4875.3 2370.15  4880.4 2369.73  4897.8 2364.46  4928.2 2359.07
  4960.0 2355.86  4968.6 2353.45  4976.6 2352.80  4976.9 2352.30  4980.6 2352.80
  5008.7 2354.62  5045.0 2359.38  5109.1 2365.31  5155.5 2375.01  5160.5 2374.67
  5169.4 2376.43  5199.5 2384.42  5219.6 2388.09  5349.5 2393.72  5386.4 2394.33
  5392.5 2395.46  5398.3 2394.74  5467.0 2397.67  5515.9 2397.92  5761.6 2405.40
#Mann=5,-1,0
  4475.2    0.16       0  4561.1    0.07       0  4594.3    0.16       0
  4976.6    0.07       0  4980.6    0.16       0
Bank Sta=4976.6,4980.6
Exp/Cntr=0.3,0.1

Type RM Length L Ch R = 1,1310,513,513,513
BEGIN DESCRIPTION:
elmc274
END DESCRIPTION:
XS GIS Cut Line= 3
      1479670.27      6779911.26      1480496.66      6780293.21
      1480746.68      6780442.52
#Sta/Elev= 30
  4540.9 2397.48  4594.2 2396.26  4737.3 2389.26  4821.5 2380.82  4879.8 2371.36
  4909.7 2364.76  4920.7 2363.33  4926.3 2360.93  4942.7 2357.52  4949.2 2354.92
  4998.6 2345.97  4998.9 2345.47  5002.6 2345.97  5008.8 2348.05  5052.9 2351.57
  5184.1 2356.05  5207.0 2358.96  5251.2 2367.76  5281.3 2375.58  5286.8 2378.10
  5309.8 2385.10  5332.7 2387.50  5350.9 2388.19  5384.1 2390.70  5424.4 2391.14
  5519.2 2395.42  5554.2 2395.75  5569.8 2397.11  5670.9 2400.09  5742.5 2400.98
#Mann=5,-1,0
  4540.9    0.16       0  4879.8    0.07       0  4998.6    0.07       0
  5002.6    0.07       0  5350.9    0.16       0
Bank Sta=4998.6,5002.6
Exp/Cntr=0.3,0.1

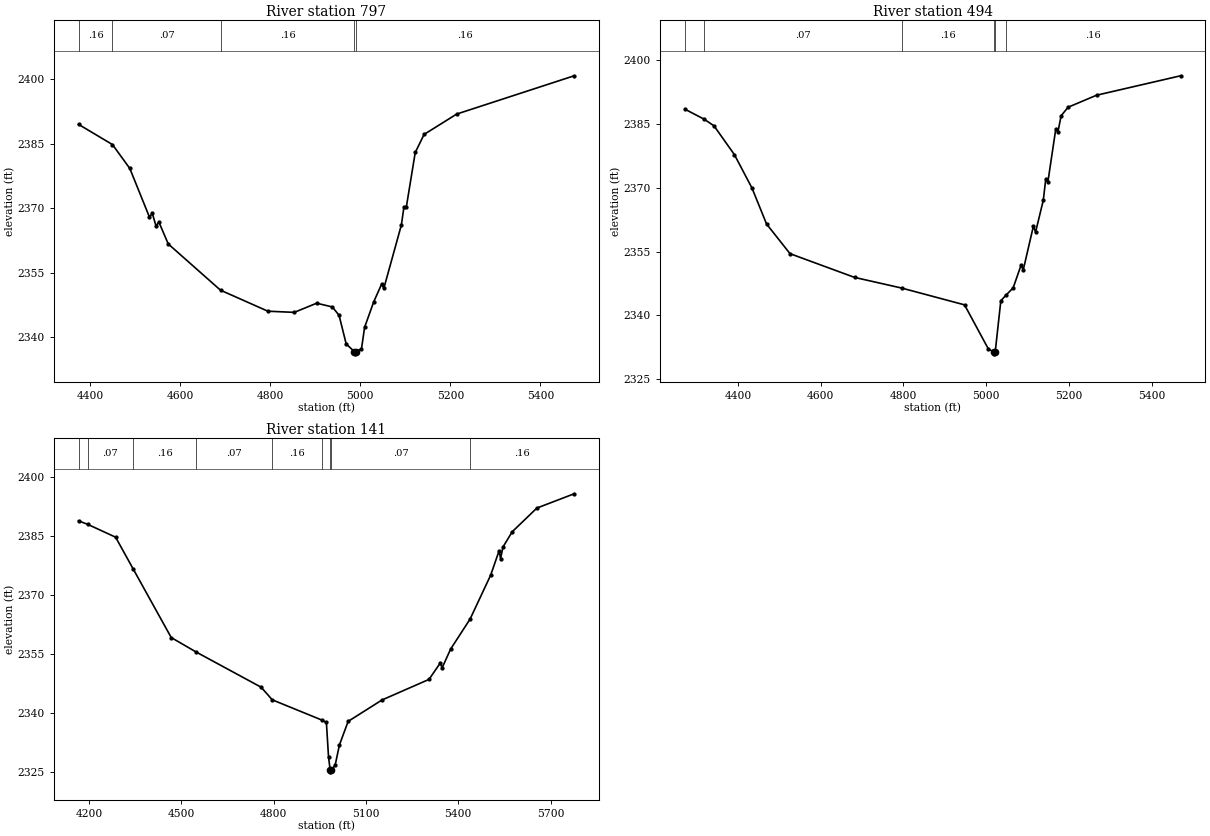
Type RM Length L Ch R = 1,797,303,303,303
BEGIN DESCRIPTION:
elmc273
END DESCRIPTION:
XS GIS Cut Line= 3
      1479656.35      6780206.38      1479930.69      6780414.74
      1480670.18      6780570.97
#Sta/Elev= 30
  4374.6 2389.52  4450.0 2384.81  4488.5 2379.25  4532.1 2367.93  4538.4 2368.82
  4546.7 2365.85  4552.9 2366.81  4573.8 2361.69  4689.8 2350.93  4795.0 2346.04
  4853.5 2345.77  4903.3 2347.90  4938.1 2347.03  4953.0 2345.09  4968.8 2338.42
  4987.2 2336.62  4987.5 2336.12  4991.2 2336.62  5002.8 2337.31  5009.7 2342.30
  5030.1 2348.26  5047.4 2352.32  5052.5 2351.40  5091.4 2366.14  5097.1 2370.36
  5102.2 2370.20  5122.1 2382.97  5141.8 2387.18  5214.1 2391.91  5474.9 2400.82
#Mann=5,-1,0
  4374.6    0.16       0  4450.0    0.07       0  4689.8    0.16       0
  4987.2    0.07       0  4991.2    0.16       0
Bank Sta=4987.2,4991.2
Exp/Cntr=0.3,0.1

Type RM Length L Ch R = 1,494,353,353,353
BEGIN DESCRIPTION:
elmc272
END DESCRIPTION:
XS GIS Cut Line= 3
      1479649.47      6780244.63      1480107.77      6780741.13
      1480593.92      6780932.11
#Sta/Elev= 30
  4272.2 2388.43  4318.8 2386.07  4342.4 2384.52  4391.7 2377.76  4434.2 2369.91
  4469.4 2361.47  4526.1 2354.51  4682.0 2348.94  4796.1 2346.43  4947.9 2342.49
  5005.8 2332.08  5018.1 2331.49  5018.4 2330.99  5022.1 2331.49  5035.6 2343.45
  5047.8 2344.74  5065.4 2346.47  5084.5 2351.81  5089.8 2350.68  5114.3 2360.96
  5119.6 2359.58  5138.3 2367.08  5144.1 2371.96  5149.4 2371.38  5168.5 2383.84
  5173.8 2383.16  5181.3 2386.89  5198.3 2388.90  5267.2 2391.72  5470.2 2396.28
#Mann=6,-1,0
  4272.2    0.16       0  4318.8    0.07       0  4796.1    0.16       0
  5018.1    0.07       0  5022.1    0.16       0  5047.8    0.16       0
Bank Sta=5018.1,5022.1
Exp/Cntr=0.3,0.1

Type RM Length L Ch R = 1,141,0,0,0
BEGIN DESCRIPTION:
elmc271
END DESCRIPTION:
XS GIS Cut Line= 4
      1479632.08      6780248.08      1479680.69      6780758.49
      1479986.25      6781070.99      1480645.96      6781105.71
#Sta/Elev= 30
  4166.2 2388.87  4195.8 2387.99  4286.7 2384.71  4343.0 2376.74  4467.5 2359.16
  4548.1 2355.50  4759.5 2346.53  4795.7 2343.32  4956.7 2338.17  4971.6 2337.55
  4978.6 2328.68  4983.8 2325.49  4984.0 2324.99  4987.8 2325.49  4999.9 2326.64
  5013.9 2331.82  5042.2 2337.83  5152.0 2343.27  5305.0 2348.52  5342.3 2352.77
  5347.3 2351.41  5375.1 2356.22  5438.4 2363.87  5505.3 2375.05  5532.6 2381.22
  5537.6 2379.27  5545.3 2382.22  5575.4 2386.10  5655.5 2392.13  5776.6 2395.76
#Mann=9,-1,0
  4166.2    0.16       0  4195.8    0.07       0  4343.0    0.16       0
  4548.1    0.07       0  4795.7    0.16       0  4956.7    0.07       0
  4983.8    0.07       0  4987.8    0.07       0  5438.4    0.16       0
Bank Sta=4983.8,4987.8
Exp/Cntr=0.3,0.1

Chan Stop Cuts=-1