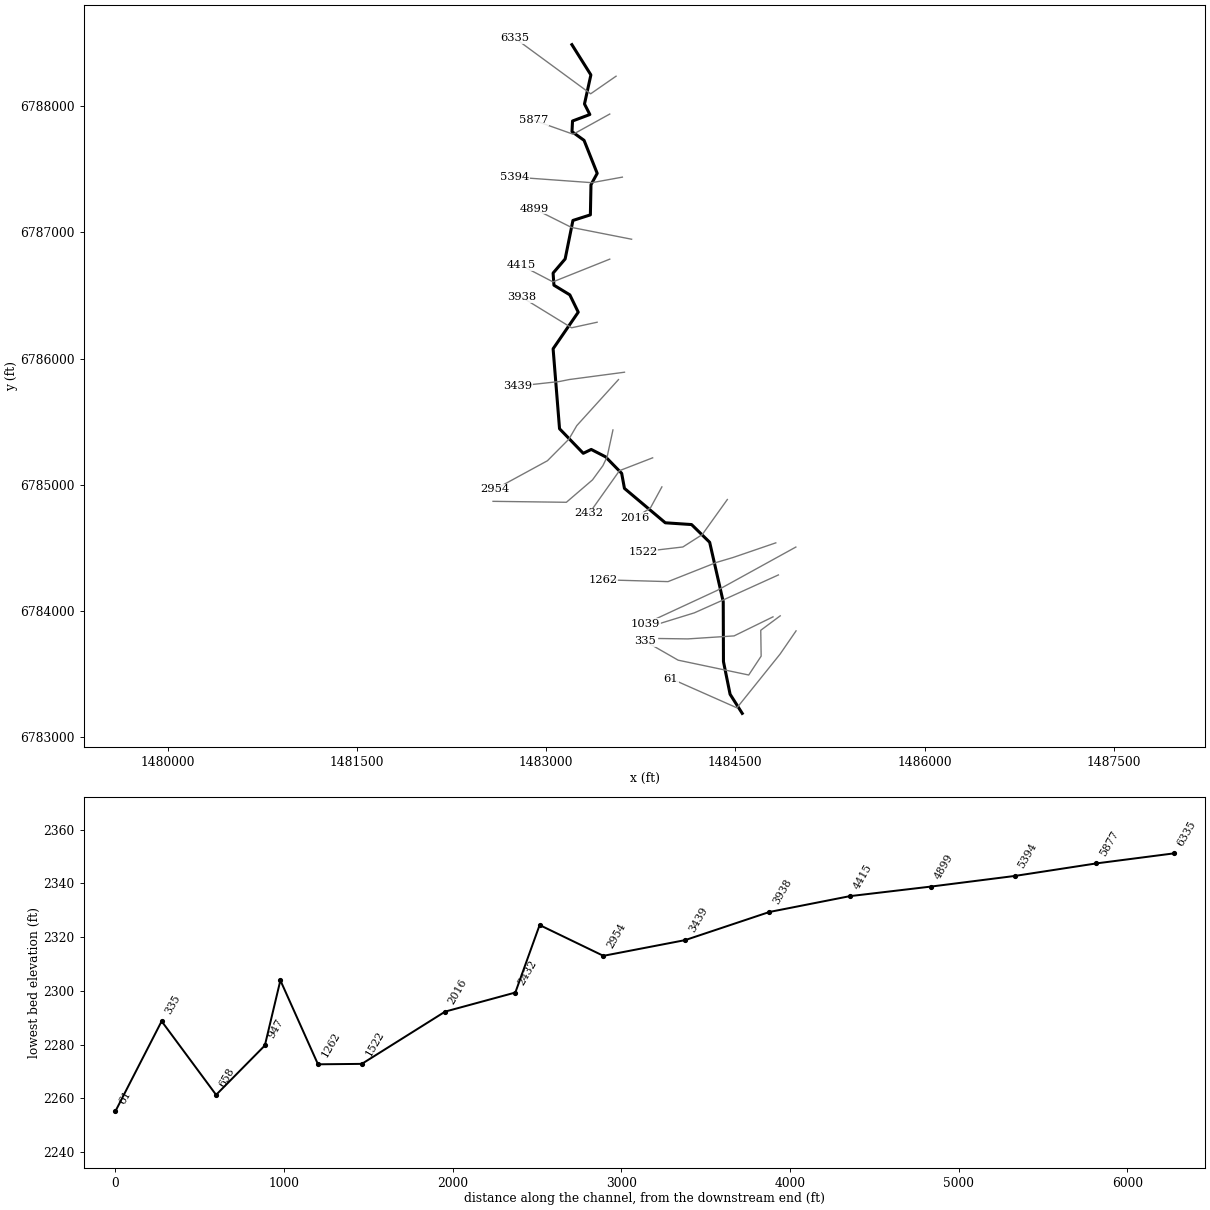
--- Elm 16.prj (project) ---

Proj Title=Elm 16 Base Level Engineering
Current Plan=p01
Default Exp/Contr=0.3,0.1
English Units
Geom File=g01
Flow File=f01
Plan File=p01
BEGIN DESCRIPTION:
Elm 16
END DESCRIPTION:

--- Elm 16.p01 (plan) ---

Plan Title=Multiple Run
Short Identifier=Multiple
Geom File=g01
Flow File=f01
Subcritical Flow
K Sum by GR= 0
Std Step Tol= 0.01
Critical Tol= 0.01
Num of Std Step Trials= 20
Max Error Tol= 0.3
Flow Tol Ratio= 0.001
Split Flow NTrial= 30
Split Flow Tol= 0.02
Split Flow Ratio= 0.02
Log Output Level= 0
Friction Slope Method= 1
Unsteady Friction Slope Method= 2
Unsteady Bridges Friction Slope Method= 1
Parabolic Critical Depth
Global Vel Dist=  1 , 1 , 1
Global Log Level= 0
CheckData=True
Encroach Param= -1, 0, 0, 0
BEGIN DESCRIPTION:
Multiple Run
END DESCRIPTION:

--- Elm 16.f01 (steady flow) ---

Flow Title=Multiple
Number of Profiles=7
Profile Names=10-year,25-year,50-year,1pct_min,100-year,1pct_plu,500-year
River Rch & RM= Elm 16,Reach-1,6335
     298     422     526     407     652     898    1010
Boundary for River Rch & Prof#=Elm 16,Reach-1,1
Up Type=0
Dn Type=3
Dn Slope=0.005
Boundary for River Rch & Prof#=Elm 16,Reach-1,2
Up Type=0
Dn Type=3
Dn Slope=0.005
Boundary for River Rch & Prof#=Elm 16,Reach-1,3
Up Type=0
Dn Type=3
Dn Slope=0.005
Boundary for River Rch & Prof#=Elm 16,Reach-1,4
Up Type=0
Dn Type=3
Dn Slope=0.005
Boundary for River Rch & Prof#=Elm 16,Reach-1,5
Up Type=0
Dn Type=3
Dn Slope=0.005
Boundary for River Rch & Prof#=Elm 16,Reach-1,6
Up Type=0
Dn Type=3
Dn Slope=0.005
Boundary for River Rch & Prof#=Elm 16,Reach-1,7
Up Type=0
Dn Type=3
Dn Slope=0.005

--- Elm 16.g01 (geometry) ---

Geom Title=Existing Conditions

River Reach=Elm 16,Reach-1
Reach XY= 30
      1483205.00      6788488.00      1483355.51      6788248.21
      1483304.79      6788017.79      1483347.29      6787934.31
      1483209.96      6787882.89      1483205.84      6787798.46
      1483301.46      6787729.51      1483405.60      6787467.95
      1483356.22      6787377.50      1483351.46      6787139.00
      1483213.14      6787094.68      1483151.45      6786789.47
      1483055.93      6786677.51      1483062.64      6786581.55
      1483188.51      6786505.05      1483255.30      6786367.82
      1483056.05      6786077.57      1483107.06      6785443.85
      1483295.00      6785249.24      1483358.23      6785279.75
      1483471.67      6785221.37      1483599.48      6785090.43
      1483621.44      6784971.21      1483945.20      6784698.48
      1484153.54      6784684.46      1484296.86      6784544.06
      1484404.48      6784072.78      1484406.22      6783598.50
      1484458.74      6783339.55      1484555.00      6783188.00

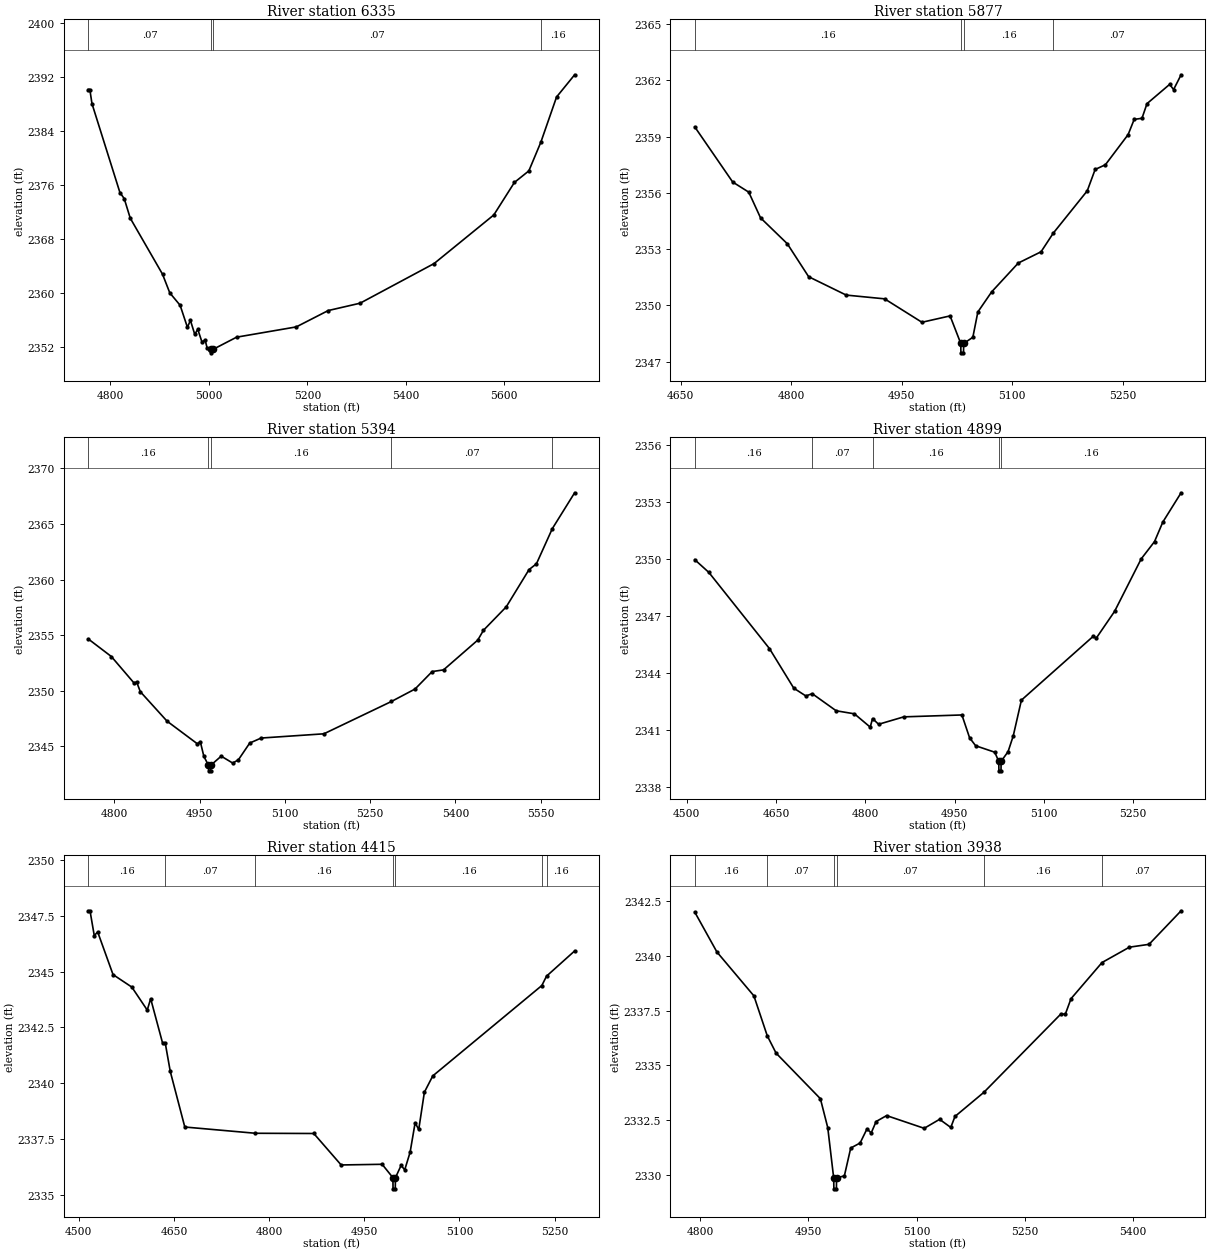
Type RM Length L Ch R = 1,6335,458,458,458
BEGIN DESCRIPTION:
404
END DESCRIPTION:
XS GIS Cut Line= 3
      1483555.03      6788238.02      1483353.76      6788098.50
      1482754.96      6788538.03
#Sta/Elev= 30
  4755.1 2390.18  4758.2 2390.18  4762.6 2388.08  4819.3 2374.93  4828.1 2374.02
  4840.3 2371.13  4905.8 2362.84  4920.6 2360.07  4941.6 2358.23  4956.4 2354.97
  4962.5 2356.00  4971.3 2353.93  4977.4 2354.67  4986.2 2352.74  4992.3 2353.12
  4996.2 2351.97  5004.1 2351.69  5004.4 2351.19  5008.1 2351.69  5056.3 2353.51
  5177.5 2355.03  5242.3 2357.45  5307.1 2358.54  5457.4 2364.41  5578.7 2371.61
  5620.5 2376.42  5649.8 2378.13  5674.2 2382.38  5706.1 2389.07  5742.8 2392.36
#Mann=4,-1,0
  4755.1    0.07       0  5004.1    0.07       0  5008.1    0.07       0
  5674.2    0.16       0
Bank Sta=5004.1,5008.1
Exp/Cntr=0.3,0.1

Type RM Length L Ch R = 1,5877,483,483,483
BEGIN DESCRIPTION:
403
END DESCRIPTION:
XS GIS Cut Line= 3
      1483504.97      6787937.98      1483215.34      6787777.96
      1482904.97      6787888.01
#Sta/Elev= 30
  4669.1 2359.52  4720.6 2356.58  4742.4 2356.04  4758.4 2354.67  4794.7 2353.29
  4823.7 2351.53  4874.7 2350.55  4926.8 2350.35  4977.5 2349.10  5015.7 2349.44
  5030.2 2347.97  5030.4 2347.47  5033.9 2347.47  5034.2 2347.97  5046.6 2348.30
  5053.4 2349.65  5072.1 2350.72  5108.3 2352.26  5139.2 2352.86  5155.7 2353.85
  5201.9 2356.11  5212.6 2357.25  5226.5 2357.50  5257.4 2359.11  5265.6 2359.92
  5276.2 2359.98  5283.0 2360.76  5313.8 2361.79  5319.1 2361.51  5329.3 2362.30
#Mann=4,-1,0
  4669.1    0.16       0  5030.2    0.07       0  5034.2    0.16       0
  5155.7    0.07       0
Bank Sta=5030.2,5034.2
Exp/Cntr=0.3,0.1

Type RM Length L Ch R = 1,5394,495,495,495
BEGIN DESCRIPTION:
402
END DESCRIPTION:
XS GIS Cut Line= 3
      1483604.99      6787438.00      1483363.15      6787394.06
      1482755.03      6787438.00
#Sta/Elev= 30
  4754.2 2354.66  4794.8 2353.08  4834.3 2350.72  4839.3 2350.78  4845.7 2349.92
  4892.7 2347.27  4946.1 2345.23  4951.2 2345.43  4957.5 2344.10  4965.6 2343.30
  4965.9 2342.80  4969.4 2342.80  4969.6 2343.30  4988.0 2344.12  5008.2 2343.50
  5018.2 2343.79  5038.2 2345.30  5058.3 2345.75  5168.6 2346.13  5287.5 2349.04
  5329.0 2350.16  5359.1 2351.73  5379.1 2351.88  5439.3 2354.56  5449.3 2355.44
  5489.4 2357.55  5529.5 2360.90  5542.5 2361.42  5570.4 2364.58  5609.7 2367.81
#Mann=5,-1,0
  4754.2    0.16       0  4965.6    0.07       0  4969.6    0.16       0
  5287.5    0.07       0  5570.4    0.16       0
Bank Sta=4965.6,4969.6
Exp/Cntr=0.3,0.1

Type RM Length L Ch R = 1,4899,484,484,484
BEGIN DESCRIPTION:
401
END DESCRIPTION:
XS GIS Cut Line= 3
      1483678.22      6786945.85      1483200.78      6787039.81
      1482905.02      6787187.99
#Sta/Elev= 30
  4513.4 2349.97  4537.1 2349.30  4639.0 2345.29  4679.8 2343.21  4700.1 2342.80
  4710.8 2342.92  4751.1 2342.02  4781.7 2341.86  4808.3 2341.16  4812.2 2341.61
  4822.4 2341.31  4864.7 2341.70  4962.4 2341.80  4975.3 2340.60  4985.5 2340.18
  5017.6 2339.84  5024.3 2339.36  5024.6 2338.86  5028.1 2338.86  5028.3 2339.36
  5040.0 2339.87  5048.7 2340.70  5062.4 2342.58  5182.8 2345.93  5188.4 2345.85
  5219.0 2347.25  5263.7 2350.01  5286.1 2350.92  5300.1 2351.95  5330.8 2353.49
#Mann=5,-1,0
  4513.4    0.16       0  4710.8    0.07       0  4812.2    0.16       0
  5024.3    0.07       0  5028.3    0.16       0
Bank Sta=5024.3,5028.3
Exp/Cntr=0.3,0.1

Type RM Length L Ch R = 1,4415,477,477,477
BEGIN DESCRIPTION:
400
END DESCRIPTION:
XS GIS Cut Line= 3
      1483504.98      6786787.99      1483054.74      6786607.95
      1482804.97      6786738.01
#Sta/Elev= 30
  4515.1 2347.73  4517.8 2347.73  4524.5 2346.62  4529.9 2346.78  4554.1 2344.87
  4583.7 2344.31  4608.0 2343.28  4613.4 2343.79  4632.2 2341.80  4636.4 2341.80
  4644.3 2340.53  4667.2 2338.04  4778.6 2337.76  4870.5 2337.75  4913.6 2336.34
  4978.2 2336.37  4995.2 2335.77  4995.4 2335.27  4998.9 2335.27  4999.2 2335.77
  5008.1 2336.32  5013.8 2336.12  5022.3 2336.91  5030.2 2338.23  5035.9 2337.93
  5044.8 2339.60  5058.0 2340.33  5229.9 2344.38  5237.3 2344.80  5281.6 2345.93
#Mann=7,-1,0
  4515.1    0.16       0  4636.4    0.07       0  4778.6    0.16       0
  4995.2    0.07       0  4999.2    0.16       0  5229.9    0.07       0
  5237.3    0.16       0
Bank Sta=4995.2,4999.2
Exp/Cntr=0.3,0.1

Type RM Length L Ch R = 1,3938,499,499,499
BEGIN DESCRIPTION:
399
END DESCRIPTION:
XS GIS Cut Line= 3
      1483404.99      6786288.00      1483202.51      6786244.04
      1482805.00      6786488.00
#Sta/Elev= 30
  4792.8 2341.99  4823.5 2340.17  4874.7 2338.17  4893.2 2336.35  4905.4 2335.56
  4966.8 2333.48  4977.0 2332.16  4985.2 2329.87  4985.5 2329.37  4989.0 2329.37
  4989.2 2329.87  5000.0 2329.96  5008.8 2331.23  5021.8 2331.46  5031.3 2332.10
  5037.2 2331.92  5044.0 2332.44  5058.5 2332.71  5110.6 2332.13  5131.9 2332.54
  5147.4 2332.17  5153.2 2332.67  5193.2 2333.77  5300.1 2337.35  5306.0 2337.33
  5313.9 2338.04  5356.9 2339.69  5394.8 2340.39  5422.0 2340.52  5466.4 2342.05
#Mann=6,-1,0
  4792.8    0.16       0  4893.2    0.07       0  4985.2    0.07       0
  4989.2    0.07       0  5193.2    0.16       0  5356.9    0.07       0
Bank Sta=4985.2,4989.2
Exp/Cntr=0.3,0.1

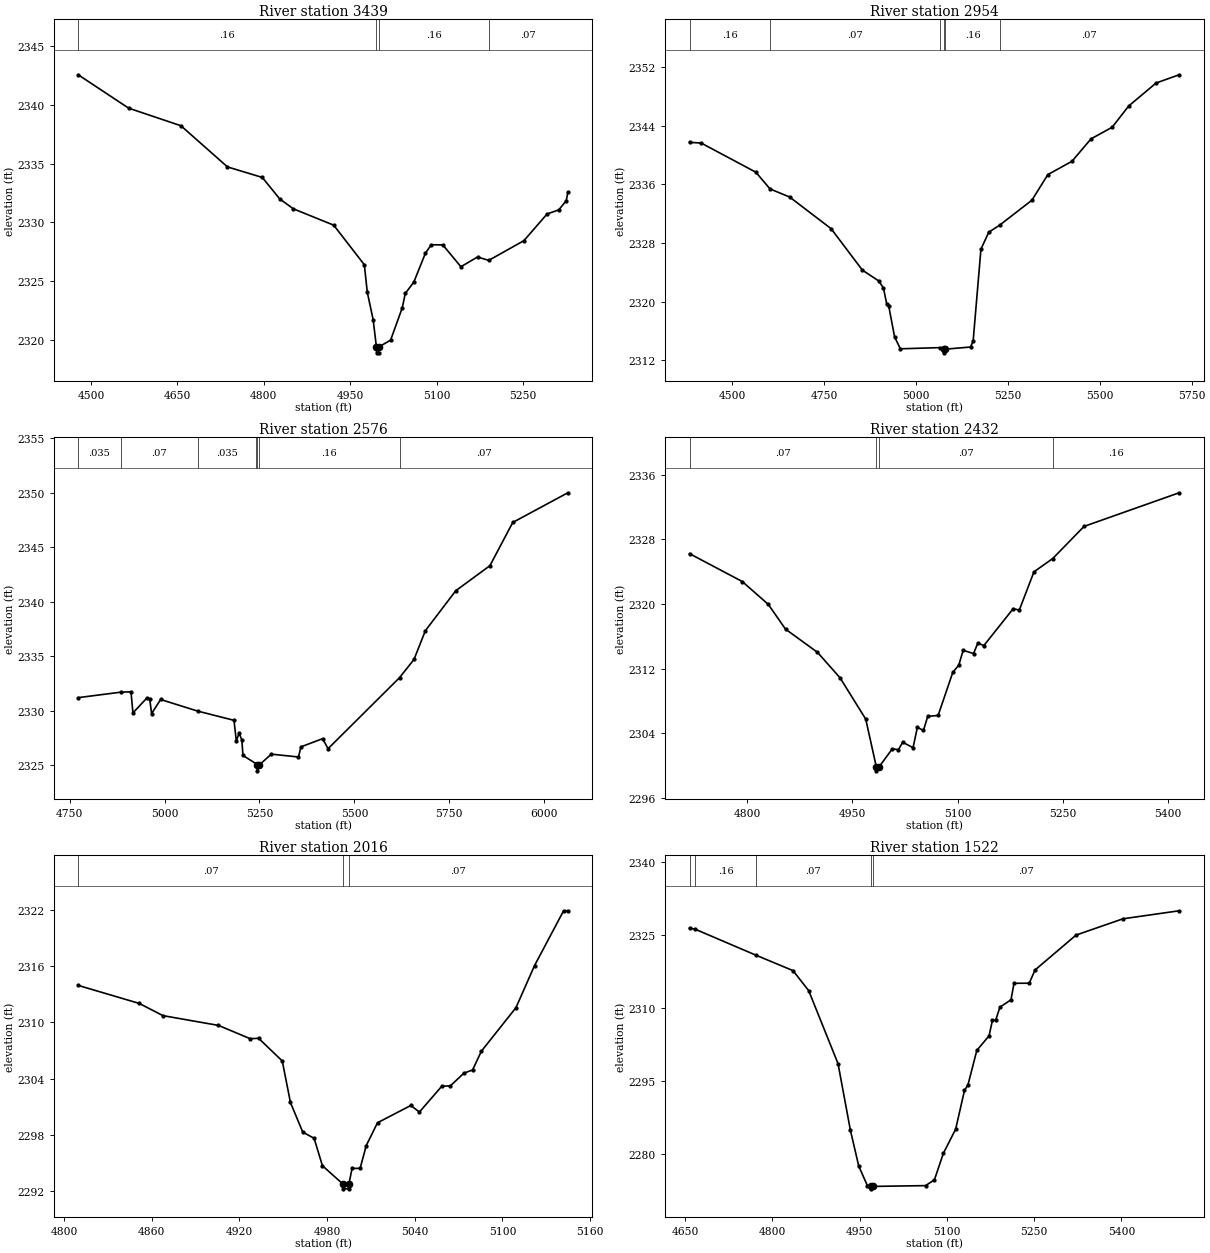
Type RM Length L Ch R = 1,3439,485,485,485
BEGIN DESCRIPTION:
398
END DESCRIPTION:
XS GIS Cut Line= 4
      1483621.72      6785891.88      1483184.42      6785833.88
      1483104.93      6785817.97      1482779.25      6785782.49
#Sta/Elev= 30
  4477.8 2342.57  4565.3 2339.73  4656.1 2338.23  4736.8 2334.73  4797.3 2333.83
  4827.6 2332.00  4851.2 2331.16  4921.2 2329.77  4974.4 2326.40  4979.5 2324.07
  4989.7 2321.72  4995.4 2319.40  4995.7 2318.90  4999.2 2318.90  4999.4 2319.40
  5020.0 2319.98  5040.2 2322.73  5045.5 2323.96  5060.3 2324.92  5080.4 2327.38
  5090.5 2328.10  5110.6 2328.09  5142.0 2326.23  5170.9 2327.06  5190.3 2326.77
  5251.4 2328.45  5291.6 2330.72  5311.8 2331.07  5324.9 2331.85  5327.6 2332.56
#Mann=4,-1,0
  4477.8    0.16       0  4995.4    0.07       0  4999.4    0.16       0
  5190.3    0.07       0
Bank Sta=4995.4,4999.4
Exp/Cntr=0.3,0.1

Type RM Length L Ch R = 1,2954,378,378,378
BEGIN DESCRIPTION:
397
END DESCRIPTION:
XS GIS Cut Line= 5
      1483574.19      6785833.38      1483243.48      6785468.23
      1483181.40      6785361.64      1483011.06      6785190.20
      1482594.50      6784963.35
#Sta/Elev= 30
  4384.0 2341.71  4415.8 2341.61  4564.5 2337.64  4603.1 2335.36  4656.4 2334.26
  4769.2 2329.95  4854.4 2324.30  4898.9 2322.83  4911.6 2321.86  4920.4 2319.72
  4926.1 2319.38  4941.9 2315.21  4957.6 2313.59  5064.5 2313.75  5075.8 2313.54
  5076.0 2313.04  5079.8 2313.54  5148.5 2313.83  5155.6 2314.65  5176.8 2327.15
  5198.0 2329.46  5227.7 2330.43  5315.3 2333.82  5359.0 2337.32  5424.5 2339.13
  5476.3 2342.18  5533.7 2343.76  5578.8 2346.66  5653.4 2349.79  5716.0 2350.91
#Mann=6,-1,0
  4384.0    0.16       0  4603.1    0.07       0  5064.5    0.16       0
  5075.8    0.07       0  5079.8    0.16       0  5227.7    0.07       0
Bank Sta=5075.8,5079.8
Exp/Cntr=0.3,0.1

Type RM Length L Ch R = 1,2576,144,144,144
BEGIN DESCRIPTION:
765
END DESCRIPTION:
XS GIS Cut Line= 6
      1483530.37      6785434.31      1483484.29      6785221.36
      1483450.91      6785151.43      1483368.26      6785038.58
      1483161.12      6784860.99      1482579.96      6784868.51
#Sta/Elev= 30
  4772.7 2331.22  4884.5 2331.72  4911.7 2331.76  4916.8 2329.82  4953.1 2331.17
  4960.9 2331.11  4966.0 2329.76  4989.7 2331.05  5087.0 2329.99  5182.9 2329.14
  5189.1 2327.23  5196.3 2327.98  5203.7 2327.32  5206.5 2325.92  5242.1 2325.14
  5244.2 2325.01  5244.5 2324.51  5248.2 2325.01  5281.3 2326.04  5352.7 2325.78
  5359.3 2326.71  5416.3 2327.46  5430.6 2326.54  5618.8 2333.05  5656.9 2334.72
  5686.9 2337.36  5766.9 2341.02  5856.9 2343.32  5917.0 2347.28  6062.0 2350.00
#Mann=7,-1,0
  4772.7   0.035       0  4884.5    0.07       0  5087.0   0.035       0
  5242.1    0.16       0  5244.2    0.07       0  5248.2    0.16       0
  5618.8    0.07       0
Bank Sta=5244.2,5248.2
Exp/Cntr=0.3,0.1

Type RM Length L Ch R = 1,2432,416,416,416
BEGIN DESCRIPTION:
396
END DESCRIPTION:
XS GIS Cut Line= 3
      1483845.07      6785213.41      1483582.12      6785111.52
      1483341.74      6784772.26
#Sta/Elev= 30
  4718.0 2326.24  4793.2 2322.79  4830.3 2319.96  4854.8 2316.90  4900.4 2314.03
  4932.6 2310.87  4969.2 2305.76  4984.2 2299.87  4984.4 2299.37  4988.2 2299.87
  5007.1 2302.10  5015.7 2301.98  5021.8 2302.91  5036.6 2302.23  5042.7 2304.74
  5051.4 2304.37  5057.5 2306.11  5072.3 2306.22  5093.2 2311.55  5101.8 2312.46
  5108.0 2314.28  5122.8 2313.88  5128.9 2315.17  5137.5 2314.87  5179.3 2319.43
  5188.0 2319.26  5208.9 2323.99  5235.6 2325.63  5280.3 2329.61  5415.8 2333.77
#Mann=4,-1,0
  4718.0    0.07       0  4984.2   0.035       0  4988.2    0.07       0
  5235.6    0.16       0
Bank Sta=4984.2,4988.2
Exp/Cntr=0.3,0.1

Type RM Length L Ch R = 1,2016,494,494,494
BEGIN DESCRIPTION:
395
END DESCRIPTION:
XS GIS Cut Line= 3
      1483918.21      6784982.98      1483827.21      6784815.74
      1483705.03      6784738.02
#Sta/Elev= 30
  4809.6 2313.94  4851.4 2312.02  4867.6 2310.72  4905.6 2309.68  4927.4 2308.26
  4933.1 2308.31  4949.3 2305.89  4954.9 2301.47  4963.3 2298.32  4971.1 2297.65
  4976.8 2294.73  4990.9 2292.77  4991.2 2292.27  4994.7 2292.27  4994.9 2292.77
  4997.1 2294.45  5002.6 2294.45  5006.8 2296.88  5014.5 2299.31  5037.3 2301.15
  5043.2 2300.45  5058.5 2303.20  5064.4 2303.24  5073.7 2304.60  5079.6 2304.93
  5085.6 2306.93  5109.3 2311.57  5122.0 2316.05  5141.9 2321.89  5144.8 2321.89
#Mann=3,-1,0
  4809.6    0.07       0  4990.9    0.07       0  4994.9    0.07       0
Bank Sta=4990.9,4994.9
Exp/Cntr=0.3,0.1

Type RM Length L Ch R = 1,1522,260,260,260
BEGIN DESCRIPTION:
394
END DESCRIPTION:
XS GIS Cut Line= 4
      1484436.95      6784882.93      1484237.70      6784604.60
      1484084.43      6784506.78      1483768.99      6784469.96
#Sta/Elev= 30
  4657.7 2326.32  4667.1 2326.14  4771.9 2320.79  4835.6 2317.62  4862.6 2313.50
  4913.0 2298.52  4934.3 2284.82  4948.6 2277.48  4963.4 2273.47  4969.2 2273.30
  4969.5 2272.80  4973.2 2273.30  5063.6 2273.46  5078.8 2274.67  5094.0 2280.07
  5115.2 2285.05  5130.4 2293.01  5136.4 2294.17  5151.6 2301.23  5172.7 2304.24
  5178.5 2307.46  5184.1 2307.46  5191.3 2310.11  5210.4 2311.64  5215.5 2315.02
  5241.7 2315.03  5251.7 2317.75  5322.2 2324.92  5402.7 2328.26  5499.4 2329.91
#Mann=5,-1,0
  4657.7    0.07       0  4667.1    0.16       0  4771.9    0.07       0
  4969.2    0.07       0  4973.2    0.07       0
Bank Sta=4969.2,4973.2
Exp/Cntr=0.3,0.1

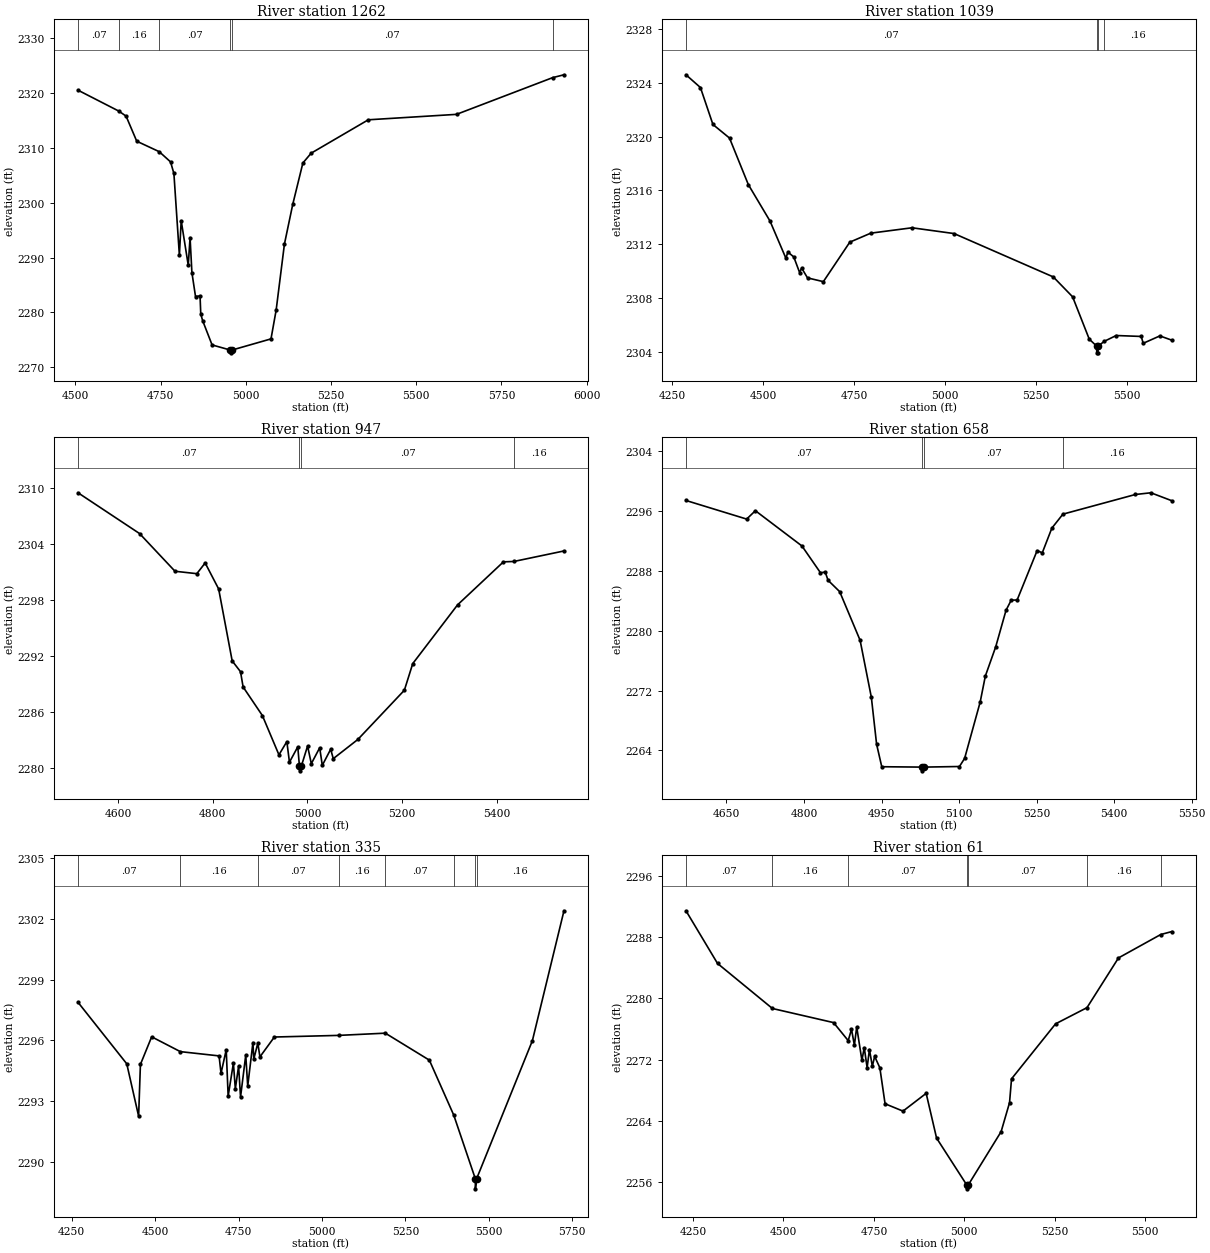
Type RM Length L Ch R = 1,1262,223,223,223
BEGIN DESCRIPTION:
764
END DESCRIPTION:
XS GIS Cut Line= 5
      1484820.98      6784539.51      1484482.43      6784423.48
      1484353.69      6784385.34      1483966.81      6784232.23
      1483449.94      6784246.84
#Sta/Elev= 30
  4508.1 2320.48  4628.2 2316.66  4649.1 2315.75  4680.3 2311.19  4746.3 2309.28
  4779.5 2307.42  4789.3 2305.31  4805.4 2290.41  4810.7 2296.72  4831.4 2288.59
  4836.7 2293.64  4842.1 2287.27  4852.7 2282.90  4866.0 2283.01  4868.1 2279.70
  4873.7 2278.49  4901.3 2274.08  4955.2 2273.14  4955.4 2272.64  4959.2 2273.14
  5074.1 2275.18  5089.2 2280.42  5113.5 2292.45  5137.9 2299.69  5167.6 2307.22
  5191.9 2309.01  5359.5 2315.09  5618.2 2316.08  5900.2 2322.77  5933.4 2323.29
#Mann=6,-1,0
  4508.1    0.07       0  4628.2    0.16       0  4746.3    0.07       0
  4955.2    0.07       0  4959.2    0.07       0  5900.2    0.16       0
Bank Sta=4955.2,4959.2
Exp/Cntr=0.3,0.1

Type RM Length L Ch R = 1,1039,92,92,92
BEGIN DESCRIPTION:
393
END DESCRIPTION:
XS GIS Cut Line= 3
      1484979.90      6784506.13      1484356.87      6784162.82
      1483788.91      6783899.47
#Sta/Elev= 30
  4287.2 2324.61  4327.0 2323.66  4361.4 2320.91  4407.0 2319.90  4458.9 2316.43
  4518.5 2313.72  4562.1 2310.96  4567.8 2311.41  4583.9 2311.05  4599.9 2309.89
  4605.6 2310.22  4621.7 2309.49  4665.3 2309.21  4738.1 2312.15  4795.9 2312.82
  4909.3 2313.22  5025.0 2312.79  5298.2 2309.56  5351.3 2308.08  5397.1 2304.93
  5417.5 2304.41  5417.7 2303.91  5421.2 2303.91  5421.5 2304.41  5438.6 2304.77
  5471.3 2305.20  5540.1 2305.13  5545.6 2304.62  5591.4 2305.17  5624.6 2304.85
#Mann=4,-1,0
  4287.2    0.07       0  5417.5    0.07       0  5421.5    0.07       0
  5438.6    0.16       0
Bank Sta=5417.5,5421.5
Exp/Cntr=0.3,0.1

Type RM Length L Ch R = 1,947,289,289,289
BEGIN DESCRIPTION:
763
END DESCRIPTION:
XS GIS Cut Line= 4
      1484841.64      6784285.21      1484399.78      6784084.94
      1484175.68      6783984.81      1483892.75      6783897.39
#Sta/Elev= 30
  4515.2 2309.52  4645.2 2305.14  4720.1 2301.09  4766.2 2300.83  4783.8 2301.98
  4812.3 2299.19  4840.9 2291.46  4858.5 2290.30  4864.0 2288.66  4904.7 2285.59
  4939.7 2281.37  4956.4 2282.79  4961.9 2280.58  4979.5 2282.23  4983.0 2280.15
  4983.2 2279.65  4987.0 2280.15  5000.2 2282.32  5008.1 2280.42  5025.8 2282.13
  5031.3 2280.24  5049.0 2281.97  5054.5 2280.96  5106.4 2283.02  5204.7 2288.31
  5222.4 2291.17  5317.1 2297.48  5414.0 2302.10  5435.9 2302.14  5541.9 2303.27
#Mann=4,-1,0
  4515.2    0.07       0  4983.0    0.07       0  4987.0    0.07       0
  5435.9    0.16       0
Bank Sta=4983,4987
Exp/Cntr=0.3,0.1

Type RM Length L Ch R = 1,658,323,323,323
BEGIN DESCRIPTION:
762
END DESCRIPTION:
XS GIS Cut Line= 4
      1484798.73      6783953.03      1484490.38      6783802.03
      1484123.23      6783778.19      1483894.31      6783781.37
#Sta/Elev= 30
  4571.6 2297.44  4689.0 2294.95  4705.9 2296.07  4796.0 2291.35  4831.8 2287.77
  4841.0 2287.86  4846.5 2286.76  4869.0 2285.24  4908.5 2278.73  4930.3 2271.09
  4940.4 2264.83  4950.4 2261.81  5028.6 2261.76  5028.8 2261.26  5032.6 2261.76
  5100.7 2261.84  5110.7 2262.92  5140.8 2270.46  5150.8 2273.94  5170.9 2277.86
  5190.9 2282.76  5200.9 2284.10  5212.3 2284.12  5251.0 2290.73  5261.0 2290.44
  5279.5 2293.74  5300.9 2295.61  5441.1 2298.24  5471.1 2298.47  5511.8 2297.40
#Mann=4,-1,0
  4571.6    0.07       0  5028.6    0.07       0  5032.6    0.07       0
  5300.9    0.16       0
Bank Sta=5028.6,5032.6
Exp/Cntr=0.3,0.1

Type RM Length L Ch R = 1,335,274,274,274
BEGIN DESCRIPTION:
761
END DESCRIPTION:
XS GIS Cut Line= 6
      1484855.95      6783960.98      1484701.77      6783846.53
      1484704.95      6783641.50      1484606.40      6783492.10
      1484046.94      6783609.71      1483786.32      6783759.09
#Sta/Elev= 30
  4269.3 2297.88  4415.3 2294.85  4450.8 2292.27  4456.2 2294.82  4489.9 2296.18
  4575.8 2295.45  4691.8 2295.24  4697.6 2294.38  4713.2 2295.54  4719.0 2293.26
  4734.7 2294.88  4740.5 2293.62  4750.3 2294.74  4756.1 2293.21  4771.7 2295.28
  4777.6 2293.75  4793.2 2295.90  4795.7 2295.08  4807.9 2295.87  4814.1 2295.19
  4857.4 2296.17  5049.6 2296.25  5189.8 2296.36  5321.7 2295.03  5394.8 2292.32
  5459.3 2289.19  5459.6 2288.69  5463.3 2289.19  5630.3 2295.99  5724.9 2302.39
#Mann=8,-1,0
  4269.3    0.07       0  4575.8    0.16       0  4807.9    0.07       0
  5049.6    0.16       0  5189.8    0.07       0  5394.8    0.16       0
  5459.3    0.07       0  5463.3    0.16       0
Bank Sta=5459.3,5463.3
Exp/Cntr=0.3,0.1

Type RM Length L Ch R = 1,61,0,0,0
BEGIN DESCRIPTION:
392
END DESCRIPTION:
XS GIS Cut Line= 4
      1484981.52      6783841.79      1484855.26      6783658.25
      1484512.91      6783231.85      1483988.30      6783464.30
#Sta/Elev= 30
  4230.4 2291.44  4317.6 2284.57  4469.4 2278.69  4638.4 2276.85  4678.9 2274.50
  4688.0 2275.97  4696.0 2273.91  4702.4 2276.28  4716.8 2271.92  4723.2 2273.59
  4731.2 2270.97  4737.6 2273.34  4745.6 2271.15  4752.0 2272.44  4766.4 2270.95
  4780.8 2266.26  4830.4 2265.30  4894.4 2267.62  4923.2 2261.78  5006.7 2255.66
  5006.9 2255.16  5010.7 2255.66  5101.6 2262.62  5124.9 2266.40  5130.4 2269.51
  5252.2 2276.69  5339.0 2278.80  5426.1 2285.29  5542.8 2288.34  5573.8 2288.73
#Mann=7,-1,0
  4230.4    0.07       0  4469.4    0.16       0  4678.9    0.07       0
  5006.7    0.07       0  5010.7    0.07       0  5339.0    0.16       0
  5542.8    0.07       0
Bank Sta=5006.7,5010.7
Exp/Cntr=0.3,0.1

Chan Stop Cuts=-1