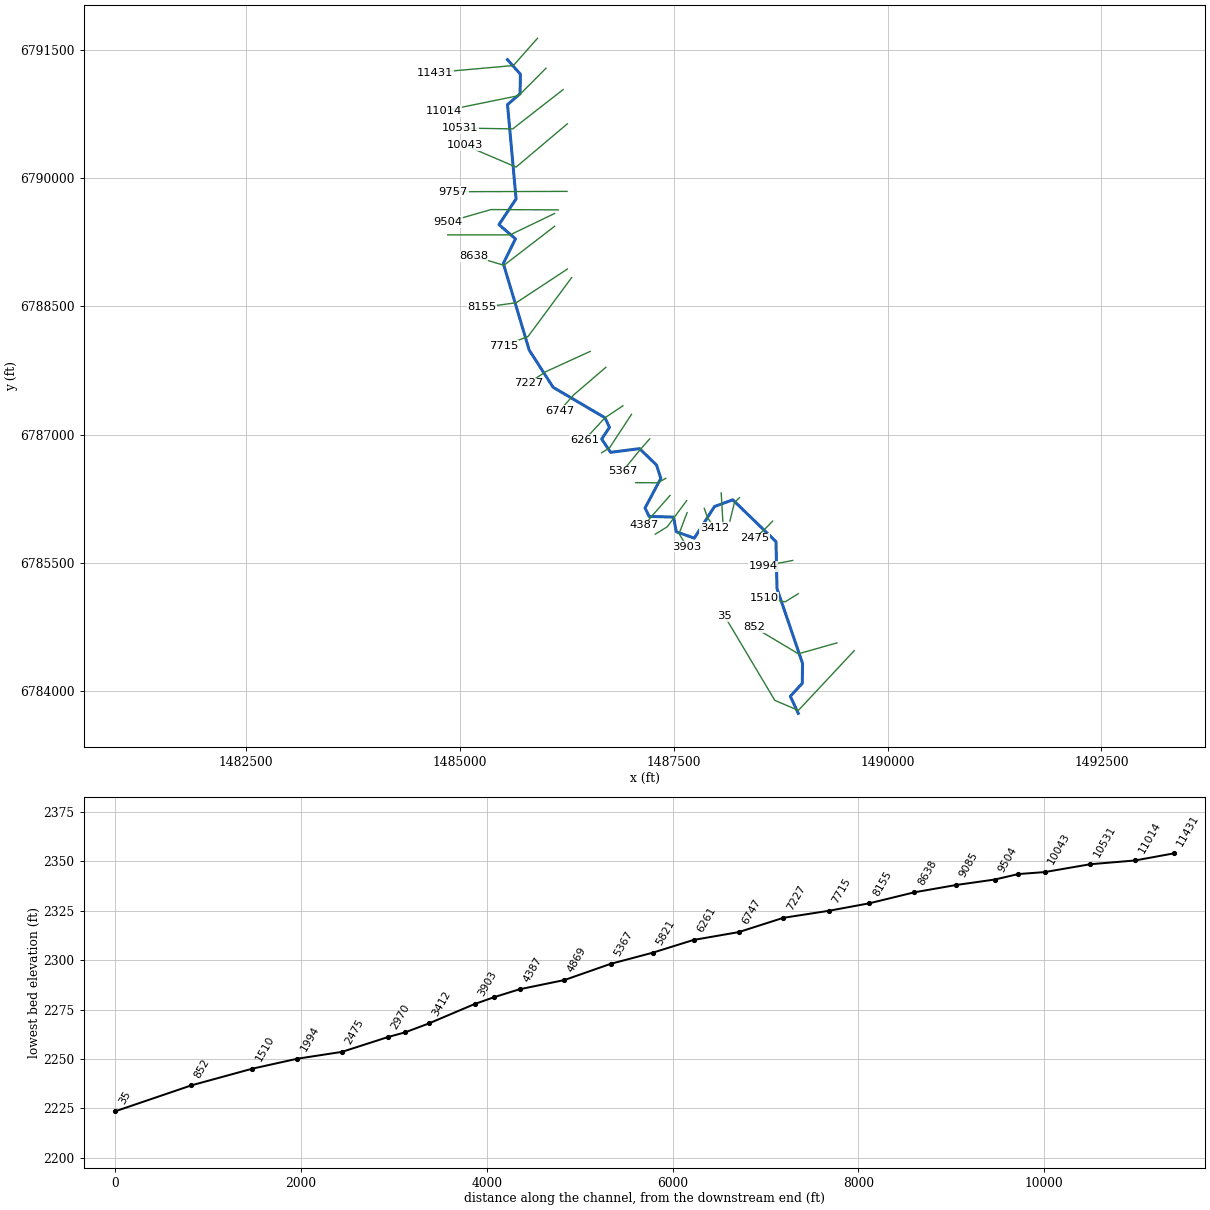
--- Elm 17.prj (project) ---

Proj Title=Elm 17 Base Level Engineering
Current Plan=p01
Default Exp/Contr=0.3,0.1
English Units
Geom File=g01
Flow File=f01
Plan File=p01
BEGIN DESCRIPTION:
Elm 17
END DESCRIPTION:

--- Elm 17.p01 (plan) ---

Plan Title=Multiple Run
Short Identifier=Multiple
Geom File=g01
Flow File=f01
Subcritical Flow
K Sum by GR= 0
Std Step Tol= 0.01
Critical Tol= 0.01
Num of Std Step Trials= 20
Max Error Tol= 0.3
Flow Tol Ratio= 0.001
Split Flow NTrial= 30
Split Flow Tol= 0.02
Split Flow Ratio= 0.02
Log Output Level= 0
Friction Slope Method= 1
Unsteady Friction Slope Method= 2
Unsteady Bridges Friction Slope Method= 1
Parabolic Critical Depth
Global Vel Dist=  1 , 1 , 1
Global Log Level= 0
CheckData=True
Encroach Param= -1, 0, 0, 0
BEGIN DESCRIPTION:
Multiple Run
END DESCRIPTION:

--- Elm 17.f01 (steady flow) ---

Flow Title=Multiple
Number of Profiles=7
Profile Names=10-year,25-year,50-year,1pct_min,100-year,1pct_plu,500-year
River Rch & RM= Elm 17,Reach-1,11431
     287     403     500     385     617     849     949
River Rch & RM= Elm 17,Reach-1,9757
     494     714     903     707    1130    1560    1800
Boundary for River Rch & Prof#=Elm 17,Reach-1,1
Up Type=0
Dn Type=3
Dn Slope=0.005
Boundary for River Rch & Prof#=Elm 17,Reach-1,2
Up Type=0
Dn Type=3
Dn Slope=0.005
Boundary for River Rch & Prof#=Elm 17,Reach-1,3
Up Type=0
Dn Type=3
Dn Slope=0.005
Boundary for River Rch & Prof#=Elm 17,Reach-1,4
Up Type=0
Dn Type=3
Dn Slope=0.005
Boundary for River Rch & Prof#=Elm 17,Reach-1,5
Up Type=0
Dn Type=3
Dn Slope=0.005
Boundary for River Rch & Prof#=Elm 17,Reach-1,6
Up Type=0
Dn Type=3
Dn Slope=0.005
Boundary for River Rch & Prof#=Elm 17,Reach-1,7
Up Type=0
Dn Type=3
Dn Slope=0.005

--- Elm 17.g01 (geometry) ---

Geom Title=Existing Conditions

River Reach=Elm 17,Reach-1
Reach XY= 30
      1485555.00      6791388.00      1485705.33      6791217.84
      1485701.62      6790989.28      1485554.64      6790863.20
      1485655.04      6789757.98      1485454.88      6789458.09
      1485647.53      6789291.62      1485505.51      6789003.22
      1485808.54      6787989.47      1486087.87      6787554.45
      1486694.25      6787197.68      1486747.21      6787084.60
      1486655.56      6786948.64      1486760.47      6786793.25
      1487099.11      6786836.04      1487297.14      6786644.17
      1487347.47      6786487.99      1487163.04      6786141.27
      1487210.38      6786043.18      1487497.09      6786035.09
      1487527.66      6785863.99      1487739.00      6785788.23
      1487974.73      6786158.51      1488188.88      6786237.51
      1488694.48      6785747.79      1488706.20      6785198.50
      1489004.91      6784322.61      1489001.97      6784089.98
      1488862.08      6783938.00      1488955.00      6783738.00

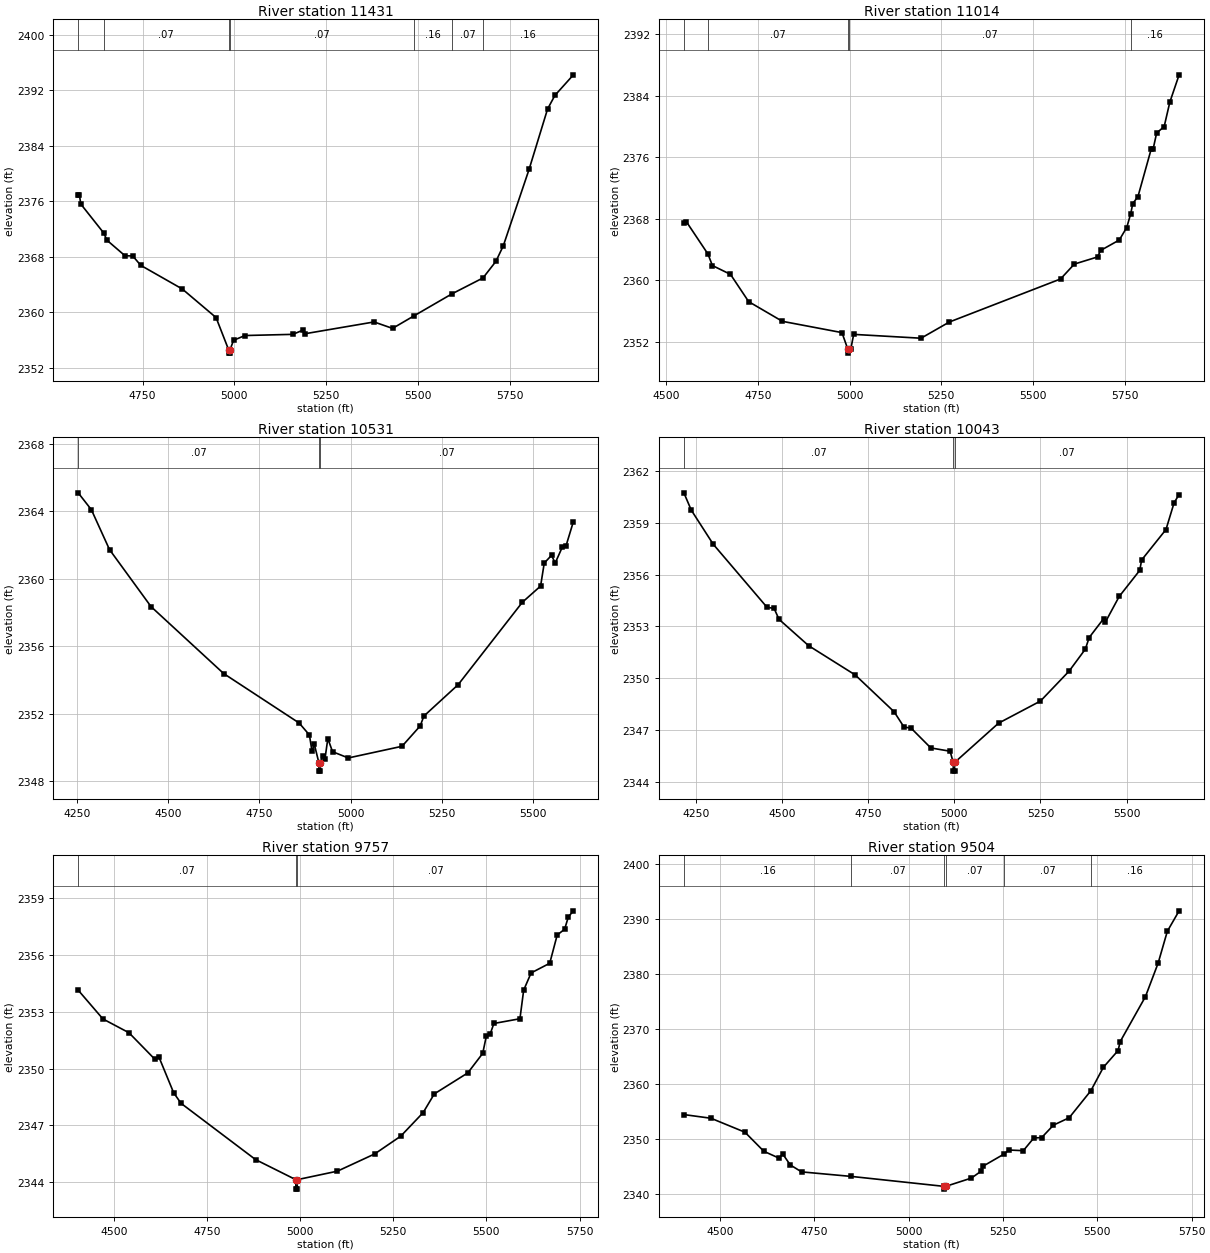
Type RM Length L Ch R = 1,11431,417,417,417
BEGIN DESCRIPTION:
248
END DESCRIPTION:
XS GIS Cut Line= 3
      1485904.98      6791637.98      1485623.44      6791319.61
      1484704.96      6791238.00
#Sta/Elev= 30
  4575.0 2376.95  4578.3 2376.95  4582.1 2375.61  4644.8 2371.41  4653.2 2370.39
  4702.5 2368.14  4723.4 2368.12  4745.2 2366.76  4858.1 2363.35  4950.1 2359.22
  4984.1 2354.59  4984.4 2354.09  4987.9 2354.09  4988.1 2354.59  4997.7 2355.94
  5028.5 2356.63  5159.1 2356.80  5185.9 2357.40  5190.9 2356.88  5379.9 2358.59
  5430.1 2357.66  5487.8 2359.45  5592.2 2362.66  5676.1 2364.94  5711.2 2367.33
  5731.3 2369.57  5801.6 2380.63  5851.8 2389.33  5871.9 2391.30  5922.1 2394.26
#Mann=7,-1,0
  4575.0    0.16       0  4644.8    0.07       0  4984.1    0.07       0
  4988.1    0.07       0  5487.8    0.16       0  5592.2    0.07       0
  5676.1    0.16       0
Bank Sta=4984.1,4988.1
Exp/Cntr=0.3,0.1

Type RM Length L Ch R = 1,11014,483,483,483
BEGIN DESCRIPTION:
247
END DESCRIPTION:
XS GIS Cut Line= 3
      1486004.98      6791287.98      1485685.57      6790967.46
      1484804.97      6790787.99
#Sta/Elev= 30
  4547.5 2367.43  4554.5 2367.60  4613.3 2363.40  4625.3 2361.91  4674.7 2360.76
  4724.3 2357.21  4816.2 2354.65  4978.8 2353.18  4994.9 2351.01  4995.1 2350.51
  4998.9 2351.01  5002.8 2351.01  5010.8 2352.95  5194.5 2352.45  5271.9 2354.56
  5575.2 2360.16  5612.9 2362.10  5676.3 2363.03  5684.4 2363.87  5735.4 2365.23
  5755.8 2366.86  5766.7 2368.66  5772.3 2369.98  5786.4 2370.88  5822.8 2377.11
  5827.9 2377.09  5837.4 2379.16  5857.9 2379.99  5873.4 2383.18  5898.7 2386.73
#Mann=5,-1,0
  4547.5    0.16       0  4613.3    0.07       0  4994.9    0.07       0
  4998.9    0.07       0  5766.7    0.16       0
Bank Sta=4994.9,4998.9
Exp/Cntr=0.3,0.1

Type RM Length L Ch R = 1,10531,488,488,488
BEGIN DESCRIPTION:
246
END DESCRIPTION:
XS GIS Cut Line= 3
      1486205.00      6791038.00      1485615.90      6790578.37
      1485004.98      6790588.00
#Sta/Elev= 30
  4252.8 2365.08  4289.0 2364.08  4338.7 2361.72  4452.7 2358.34  4651.7 2354.38
  4858.8 2351.45  4887.0 2350.74  4894.1 2349.77  4900.5 2350.18  4912.9 2349.10
  4913.2 2348.60  4916.7 2348.60  4916.9 2349.10  4923.1 2349.50  4929.4 2349.29
  4937.5 2350.53  4950.4 2349.75  4993.6 2349.38  5140.9 2350.07  5190.9 2351.28
  5200.9 2351.86  5294.9 2353.72  5471.0 2358.60  5521.0 2359.56  5531.0 2360.92
  5551.0 2361.38  5561.0 2360.92  5581.0 2361.89  5591.0 2361.96  5611.0 2363.38
#Mann=3,-1,0
  4252.8    0.07       0  4912.9    0.07       0  4916.9    0.07       0
Bank Sta=4912.9,4916.9
Exp/Cntr=0.3,0.1

Type RM Length L Ch R = 1,10043,286,286,286
BEGIN DESCRIPTION:
245
END DESCRIPTION:
XS GIS Cut Line= 3
      1486255.01      6790638.01      1485654.89      6790131.34
      1485054.99      6790388.00
#Sta/Elev= 30
  4214.6 2360.72  4236.1 2359.72  4299.8 2357.75  4455.8 2354.11  4476.6 2354.04
  4490.9 2353.41  4576.7 2351.89  4711.9 2350.20  4825.0 2348.07  4853.6 2347.19
  4874.5 2347.12  4931.6 2345.98  4987.6 2345.79  4996.7 2345.14  4997.0 2344.64
  5000.5 2344.64  5000.7 2345.14  5128.2 2347.41  5250.0 2348.69  5333.2 2350.42
  5380.3 2351.69  5391.4 2352.36  5433.0 2353.44  5438.4 2353.25  5478.5 2354.73
  5538.2 2356.24  5543.7 2356.84  5614.4 2358.60  5638.0 2360.15  5652.5 2360.62
#Mann=3,-1,0
  4214.6    0.07       0  4996.7    0.07       0  5000.7    0.07       0
Bank Sta=4996.7,5000.7
Exp/Cntr=0.3,0.1

Type RM Length L Ch R = 1,9757,253,253,253
BEGIN DESCRIPTION:
840
END DESCRIPTION:
XS GIS Cut Line= 2
      1486251.41      6789846.74      1484921.41      6789843.13
#Sta/Elev= 30
  4403.6 2354.14  4470.0 2352.62  4540.0 2351.89  4610.0 2350.48  4620.0 2350.63
  4660.0 2348.72  4680.0 2348.16  4880.0 2345.19  4988.0 2344.13  4988.3 2343.63
  4991.8 2343.63  4992.0 2344.13  5100.0 2344.58  5200.0 2345.49  5270.0 2346.43
  5330.0 2347.67  5360.0 2348.66  5450.0 2349.77  5490.0 2350.80  5500.0 2351.74
  5510.0 2351.82  5520.0 2352.38  5590.0 2352.63  5600.0 2354.14  5620.0 2355.05
  5670.0 2355.56  5690.0 2357.05  5710.0 2357.36  5720.0 2358.01  5733.6 2358.33
#Mann=3,-1,0
  4403.6    0.07       0  4988.0    0.07       0  4992.0    0.07       0
Bank Sta=4988,4992
Exp/Cntr=0.3,0.1

Type RM Length L Ch R = 1,9504,419,419,419
BEGIN DESCRIPTION:
244
END DESCRIPTION:
XS GIS Cut Line= 3
      1486146.86      6789630.47      1485361.11      6789634.08
      1484855.03      6789488.01
#Sta/Elev= 30
  4404.3 2354.43  4476.2 2353.76  4566.2 2351.22  4616.2 2347.75  4656.2 2346.51
  4666.2 2347.27  4686.2 2345.27  4716.2 2344.00  4848.4 2343.17  5094.2 2341.36
  5094.4 2340.86  5098.2 2341.36  5166.2 2342.87  5192.6 2344.15  5197.8 2345.06
  5254.0 2347.29  5265.1 2347.98  5303.9 2347.86  5331.7 2350.17  5352.5 2350.24
  5383.8 2352.51  5425.4 2353.85  5482.9 2358.77  5516.2 2363.05  5555.0 2366.08
  5560.7 2367.72  5627.5 2375.89  5661.2 2382.00  5685.6 2387.80  5716.8 2391.52
#Mann=6,-1,0
  4404.3    0.16       0  4848.4    0.07       0  5094.2    0.07       0
  5098.2    0.07       0  5254.0    0.07       0  5482.9    0.16       0
Bank Sta=5094.2,5098.2
Exp/Cntr=0.3,0.1

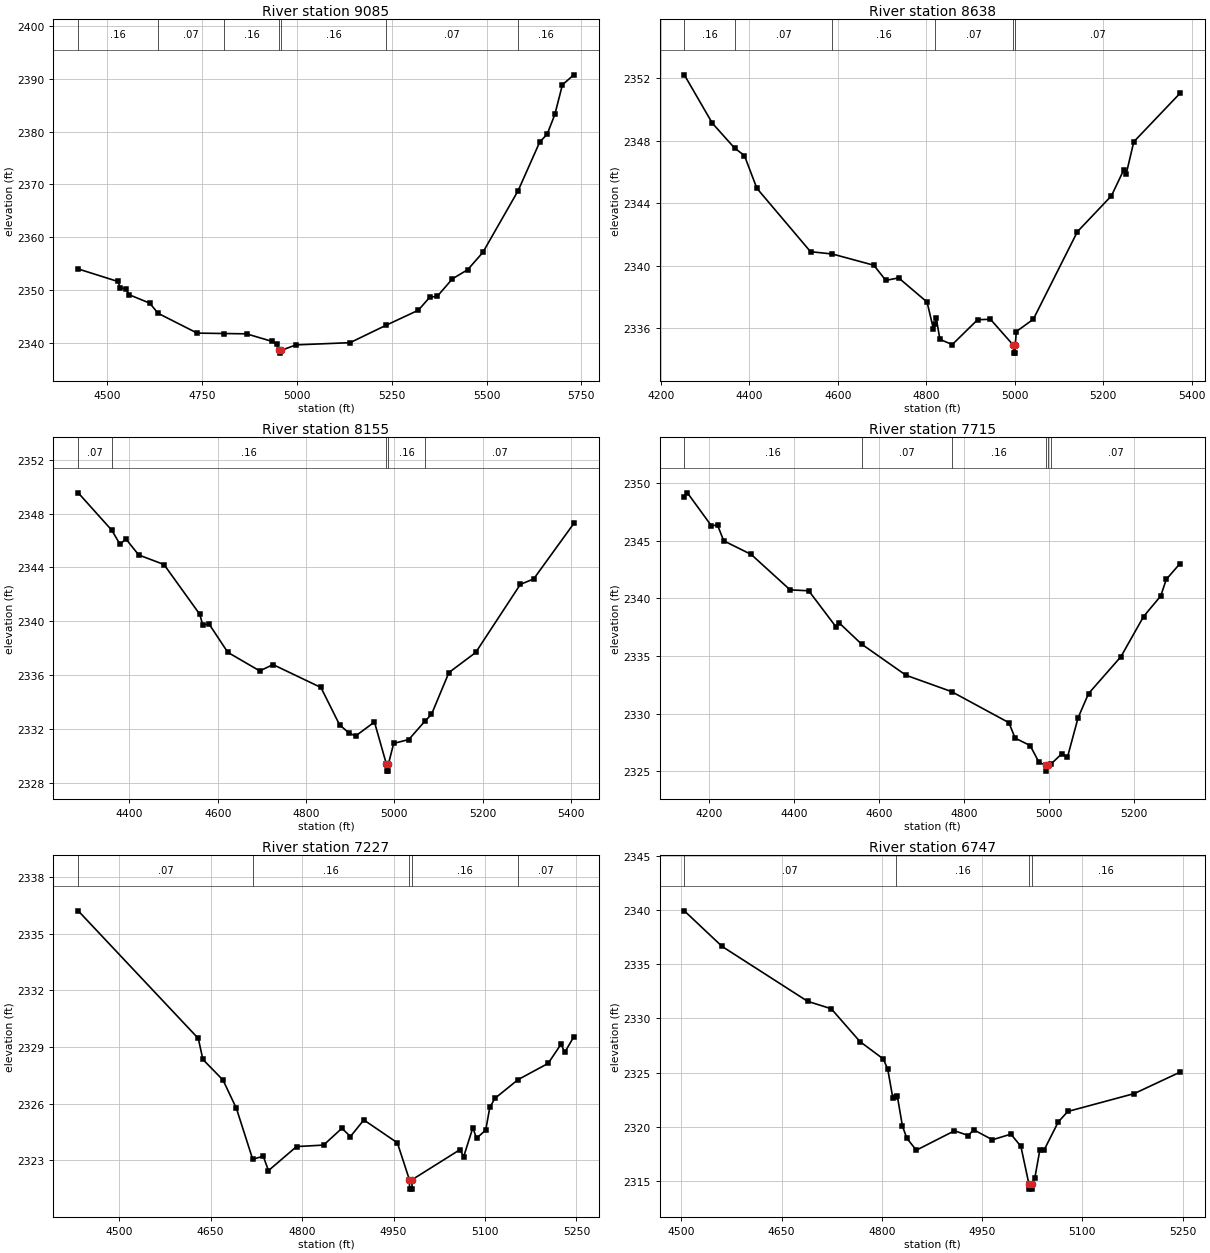
Type RM Length L Ch R = 1,9085,447,447,447
BEGIN DESCRIPTION:
243
END DESCRIPTION:
XS GIS Cut Line= 3
      1486104.96      6789587.98      1485585.02      6789337.80
      1484855.02      6789338.00
#Sta/Elev= 30
  4423.0 2354.00  4527.6 2351.63  4533.9 2350.48  4550.2 2350.16  4556.1 2349.16
  4611.6 2347.53  4633.6 2345.61  4736.8 2341.86  4808.5 2341.78  4866.9 2341.72
  4933.4 2340.31  4946.0 2339.86  4953.6 2338.57  4953.9 2338.07  4957.7 2338.57
  4997.2 2339.63  5140.0 2340.05  5235.7 2343.37  5320.0 2346.19  5350.0 2348.64
  5370.0 2348.83  5410.0 2352.14  5450.0 2353.85  5490.0 2357.12  5583.2 2368.82
  5640.0 2378.00  5660.0 2379.54  5680.0 2383.25  5700.0 2388.86  5730.0 2390.74
#Mann=7,-1,0
  4423.0    0.16       0  4633.6    0.07       0  4808.5    0.16       0
  4953.6    0.07       0  4957.7    0.16       0  5235.7    0.07       0
  5583.2    0.16       0
Bank Sta=4953.6,4957.7
Exp/Cntr=0.3,0.1

Type RM Length L Ch R = 1,8638,483,483,483
BEGIN DESCRIPTION:
242
END DESCRIPTION:
XS GIS Cut Line= 3
      1486105.01      6789438.01      1485513.14      6788981.95
      1485155.01      6789088.00
#Sta/Elev= 30
  4252.8 2352.22  4316.2 2349.12  4366.4 2347.53  4388.7 2347.05  4416.9 2344.95
  4538.2 2340.89  4587.7 2340.74  4681.4 2340.02  4708.5 2339.05  4737.5 2339.21
  4801.8 2337.66  4816.3 2335.91  4819.4 2336.26  4822.6 2336.62  4830.8 2335.27
  4858.8 2334.94  4916.0 2336.53  4945.0 2336.56  4997.1 2334.89  4997.3 2334.39
  5000.9 2334.39  5001.2 2334.89  5003.5 2335.77  5042.0 2336.56  5141.7 2342.17
  5218.7 2344.47  5246.7 2346.14  5251.9 2345.85  5269.2 2347.93  5373.5 2351.03
#Mann=6,-1,0
  4252.8    0.16       0  4366.4    0.07       0  4587.7    0.16       0
  4819.4    0.07       0  4997.1    0.07       0  5001.2    0.07       0
Bank Sta=4997.1,5001.2
Exp/Cntr=0.3,0.1

Type RM Length L Ch R = 1,8155,440,440,440
BEGIN DESCRIPTION:
241
END DESCRIPTION:
XS GIS Cut Line= 3
      1486254.96      6788937.98      1485657.36      6788543.98
      1485255.03      6788488.00
#Sta/Elev= 30
  4284.2 2349.54  4360.5 2346.75  4379.0 2345.70  4392.0 2346.12  4421.2 2344.92
  4478.4 2344.21  4559.6 2340.50  4565.7 2339.75  4580.8 2339.77  4622.9 2337.68
  4695.2 2336.30  4725.3 2336.77  4833.7 2335.07  4875.8 2332.30  4896.9 2331.69
  4912.0 2331.46  4954.9 2332.50  4982.1 2329.35  4982.4 2328.85  4986.1 2328.85
  4986.3 2329.35  4998.4 2330.91  5032.7 2331.20  5069.0 2332.56  5083.9 2333.06
  5123.5 2336.18  5184.1 2337.67  5285.1 2342.73  5315.4 2343.14  5406.2 2347.26
#Mann=5,-1,0
  4284.2    0.07       0  4360.5    0.16       0  4982.1    0.07       0
  4986.3    0.16       0  5069.0    0.07       0
Bank Sta=4982.1,4986.3
Exp/Cntr=0.3,0.1

Type RM Length L Ch R = 1,7715,488,488,488
BEGIN DESCRIPTION:
240
END DESCRIPTION:
XS GIS Cut Line= 3
      1486305.02      6788838.03      1485794.20      6788147.67
      1485505.00      6788038.00
#Sta/Elev= 30
  4141.2 2348.82  4148.5 2349.14  4204.9 2346.29  4219.5 2346.35  4234.1 2344.98
  4298.8 2343.80  4390.6 2340.73  4434.5 2340.65  4499.2 2337.50  4505.5 2337.89
  4559.0 2336.03  4663.7 2333.33  4771.2 2331.91  4906.2 2329.22  4920.9 2327.88
  4956.3 2327.24  4977.2 2325.78  4994.5 2325.52  4994.8 2325.02  4998.8 2325.52
  5005.7 2325.64  5031.2 2326.54  5044.3 2326.23  5069.1 2329.62  5093.9 2331.74
  5170.3 2334.94  5223.7 2338.42  5264.1 2340.20  5277.2 2341.64  5309.3 2343.00
#Mann=6,-1,0
  4141.2    0.16       0  4559.0    0.07       0  4771.2    0.16       0
  4994.5    0.07       0  4998.8    0.16       0  5005.7    0.07       0
Bank Sta=4994.5,4998.8
Exp/Cntr=0.3,0.1

Type RM Length L Ch R = 1,7227,480,480,480
BEGIN DESCRIPTION:
239
END DESCRIPTION:
XS GIS Cut Line= 3
      1486520.97      6787974.18      1486005.15      6787738.06
      1485799.77      6787603.38
#Sta/Elev= 30
  4432.7 2336.20  4629.7 2329.45  4637.2 2328.34  4670.2 2327.25  4692.2 2325.75
  4718.9 2323.06  4736.2 2323.22  4744.8 2322.46  4790.8 2323.73  4835.2 2323.81
  4865.3 2324.70  4879.2 2324.26  4901.2 2325.14  4956.2 2323.93  4975.9 2321.98
  4976.2 2321.48  4980.1 2321.48  4980.4 2321.98  5059.0 2323.57  5064.9 2323.19
  5080.0 2324.73  5086.0 2324.17  5101.1 2324.60  5107.8 2325.80  5116.2 2326.28
  5154.1 2327.27  5203.5 2328.13  5224.7 2329.15  5230.7 2328.71  5245.6 2329.54
#Mann=5,-1,0
  4432.7    0.07       0  4718.9    0.16       0  4975.9    0.07       0
  4980.4    0.16       0  5154.1    0.07       0
Bank Sta=4975.9,4980.4
Exp/Cntr=0.3,0.1

Type RM Length L Ch R = 1,6747,486,486,486
BEGIN DESCRIPTION:
238
END DESCRIPTION:
XS GIS Cut Line= 3
      1486704.99      6787787.99      1486328.84      6787465.15
      1486164.97      6787281.54
#Sta/Elev= 30
  4504.3 2339.91  4560.8 2336.63  4688.8 2331.57  4724.3 2330.88  4767.1 2327.86
  4802.2 2326.25  4808.8 2325.31  4816.5 2322.62  4821.5 2322.79  4823.1 2322.84
  4830.8 2320.06  4837.4 2318.94  4851.6 2317.84  4908.7 2319.63  4929.6 2319.19
  4937.2 2319.73  4965.5 2318.80  4993.2 2319.32  5008.1 2318.19  5020.0 2314.75
  5020.3 2314.25  5024.2 2314.25  5024.5 2314.75  5029.0 2315.29  5036.4 2317.84
  5043.2 2317.90  5064.1 2320.45  5078.3 2321.41  5177.8 2323.06  5246.1 2325.03
#Mann=4,-1,0
  4504.3    0.07       0  4821.5    0.16       0  5020.0    0.07       0
  5024.5    0.16       0
Bank Sta=5020,5024.5
Exp/Cntr=0.3,0.1

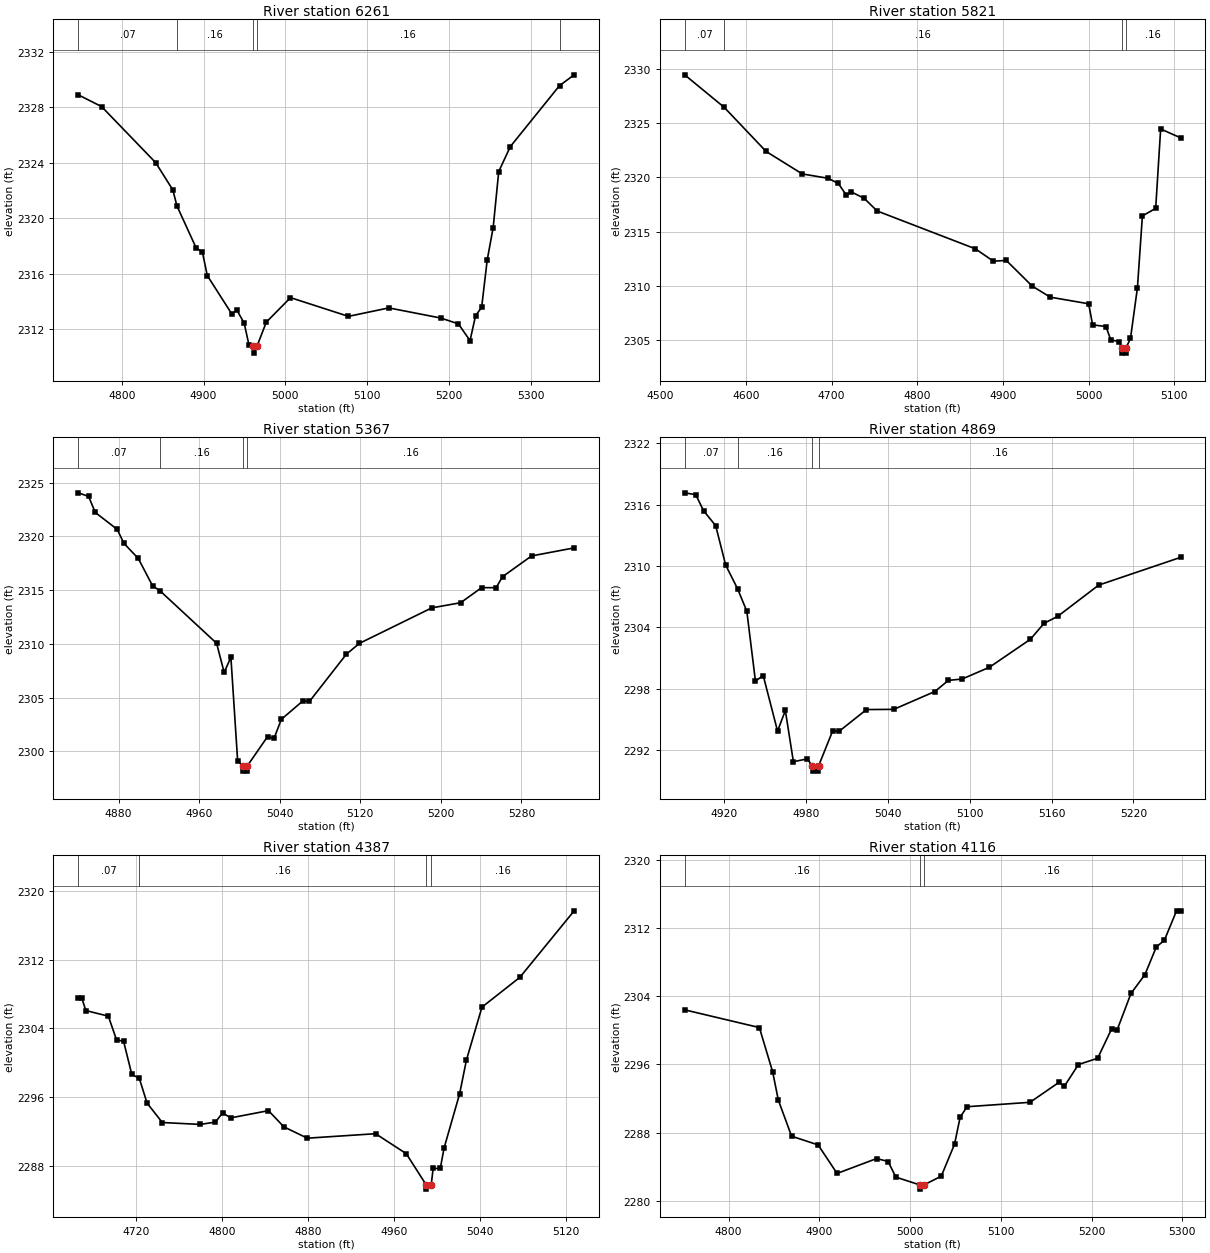
Type RM Length L Ch R = 1,6261,440,440,440
BEGIN DESCRIPTION:
237
END DESCRIPTION:
XS GIS Cut Line= 3
      1486905.01      6787338.01      1486694.25      6787197.68
      1486455.00      6786938.00
#Sta/Elev= 30
  4746.8 2328.91  4775.4 2328.06  4841.5 2324.02  4862.5 2322.05  4867.5 2320.90
  4891.0 2317.87  4898.6 2317.58  4904.6 2315.88  4934.6 2313.11  4940.7 2313.40
  4949.7 2312.45  4955.7 2310.84  4960.8 2310.79  4961.1 2310.29  4965.4 2310.79
  4976.7 2312.52  5006.3 2314.29  5077.2 2312.94  5126.5 2313.55  5190.0 2312.82
  5211.6 2312.40  5225.8 2311.19  5232.6 2312.99  5240.0 2313.59  5246.8 2317.00
  5254.1 2319.34  5260.9 2323.38  5275.1 2325.18  5335.2 2329.57  5353.1 2330.35
#Mann=5,-1,0
  4746.8    0.07       0  4867.5    0.16       0  4960.8    0.07       0
  4965.4    0.16       0  5335.2    0.07       0
Bank Sta=4960.8,4965.4
Exp/Cntr=0.3,0.1

Type RM Length L Ch R = 1,5821,454,454,454
BEGIN DESCRIPTION:
236
END DESCRIPTION:
XS GIS Cut Line= 3
      1487005.01      6787238.01      1486746.68      6786843.70
      1486654.97      6786787.98
#Sta/Elev= 30
  4528.6 2329.44  4574.7 2326.45  4623.6 2322.39  4665.8 2320.32  4696.0 2319.92
  4707.9 2319.44  4717.1 2318.38  4723.0 2318.67  4738.1 2318.07  4753.2 2316.91
  4867.8 2313.43  4888.8 2312.29  4903.9 2312.36  4934.1 2310.00  4955.2 2308.98
  5000.0 2308.37  5004.6 2306.43  5020.1 2306.28  5025.9 2305.04  5035.5 2304.90
  5039.0 2304.33  5039.4 2303.83  5043.4 2303.83  5043.7 2304.33  5048.8 2305.18
  5056.9 2309.84  5062.7 2316.46  5078.2 2317.15  5084.0 2324.46  5107.3 2323.64
#Mann=4,-1,0
  4528.6    0.07       0  4574.7    0.16       0  5039.0    0.07       0
  5043.7    0.16       0
Bank Sta=5039,5043.7
Exp/Cntr=0.3,0.1

Type RM Length L Ch R = 1,5367,498,498,498
BEGIN DESCRIPTION:
235
END DESCRIPTION:
XS GIS Cut Line= 3
      1487217.37      6786950.05      1487111.17      6786830.24
      1486901.30      6786572.60
#Sta/Elev= 30
  4839.9 2324.05  4850.2 2323.72  4856.8 2322.23  4878.6 2320.65  4885.3 2319.35
  4899.5 2317.95  4913.7 2315.41  4921.2 2314.93  4977.3 2310.06  4984.8 2307.35
  4991.5 2308.75  4998.2 2299.12  5003.2 2298.67  5003.6 2298.17  5007.6 2298.17
  5007.9 2298.67  5027.9 2301.38  5034.3 2301.21  5041.6 2302.99  5063.1 2304.71
  5069.5 2304.65  5106.1 2309.04  5119.1 2310.05  5190.9 2313.35  5219.6 2313.83
  5240.4 2315.23  5254.8 2315.23  5261.2 2316.25  5290.0 2318.18  5332.3 2318.93
#Mann=4,-1,0
  4839.9    0.07       0  4921.2    0.16       0  5003.2    0.07       0
  5007.9    0.16       0
Bank Sta=5003.2,5007.9
Exp/Cntr=0.3,0.1

Type RM Length L Ch R = 1,4869,482,482,482
BEGIN DESCRIPTION:
234
END DESCRIPTION:
XS GIS Cut Line= 3
      1487404.99      6786487.99      1487309.45      6786436.35
      1487054.96      6786438.00
#Sta/Elev= 30
  4891.4 2317.14  4899.5 2316.96  4905.2 2315.40  4914.1 2313.93  4921.4 2310.09
  4930.1 2307.78  4936.9 2305.58  4943.2 2298.76  4948.9 2299.30  4959.4 2293.88
  4965.1 2295.89  4971.0 2290.89  4981.3 2291.17  4984.7 2290.47  4985.0 2289.97
  4989.0 2289.97  4989.4 2290.47  4999.7 2293.88  5004.7 2293.88  5024.5 2295.98
  5044.5 2296.00  5074.5 2297.74  5084.5 2298.83  5094.5 2298.96  5114.5 2300.11
  5144.5 2302.84  5154.5 2304.40  5164.5 2305.08  5194.5 2308.13  5254.5 2310.84
#Mann=4,-1,0
  4891.4    0.07       0  4930.1    0.16       0  4984.7    0.07       0
  4989.4    0.16       0
Bank Sta=4984.7,4989.4
Exp/Cntr=0.3,0.1

Type RM Length L Ch R = 1,4387,271,271,271
BEGIN DESCRIPTION:
233
END DESCRIPTION:
XS GIS Cut Line= 3
      1487454.99      6786287.99      1487234.55      6786037.46
      1487154.97      6785937.97
#Sta/Elev= 30
  4666.3 2307.53  4669.6 2307.53  4673.4 2306.07  4694.3 2305.42  4701.9 2302.68
  4708.5 2302.49  4716.1 2298.66  4723.1 2298.19  4730.3 2295.32  4744.5 2293.06
  4779.7 2292.84  4793.9 2293.11  4800.5 2294.18  4808.1 2293.60  4843.2 2294.44
  4857.5 2292.56  4879.3 2291.24  4942.8 2291.76  4971.3 2289.44  4989.8 2285.82
  4990.1 2285.32  4994.5 2285.82  4996.3 2287.72  5002.9 2287.72  5006.5 2290.11
  5020.9 2296.39  5027.3 2300.35  5041.7 2306.47  5076.9 2309.93  5127.4 2317.66
#Mann=4,-1,0
  4666.3    0.07       0  4723.1    0.16       0  4989.8    0.07       0
  4994.5    0.16       0
Bank Sta=4989.8,4994.5
Exp/Cntr=0.3,0.1

Type RM Length L Ch R = 1,4116,213,213,213
BEGIN DESCRIPTION:
839
END DESCRIPTION:
XS GIS Cut Line= 3
      1487649.89      6786227.96      1487422.81      6785921.58
      1487282.25      6785835.08
#Sta/Elev= 30
  4751.7 2302.40  4834.0 2300.32  4848.6 2295.13  4854.9 2291.80  4869.5 2287.57
  4898.7 2286.55  4919.6 2283.20  4963.2 2284.95  4975.9 2284.60  4984.3 2282.77
  5010.6 2281.86  5011.0 2281.36  5015.4 2281.86  5034.4 2282.88  5049.0 2286.63
  5055.2 2289.80  5062.8 2291.03  5132.2 2291.55  5164.2 2293.90  5170.0 2293.43
  5185.5 2295.98  5206.7 2296.72  5222.1 2300.17  5228.0 2300.00  5243.4 2304.32
  5258.8 2306.54  5271.4 2309.80  5280.1 2310.54  5293.6 2314.02  5298.1 2314.02
#Mann=3,-1,0
  4751.7    0.16       0  5010.6    0.07       0  5015.4    0.16       0
Bank Sta=5010.6,5015.4
Exp/Cntr=0.3,0.1

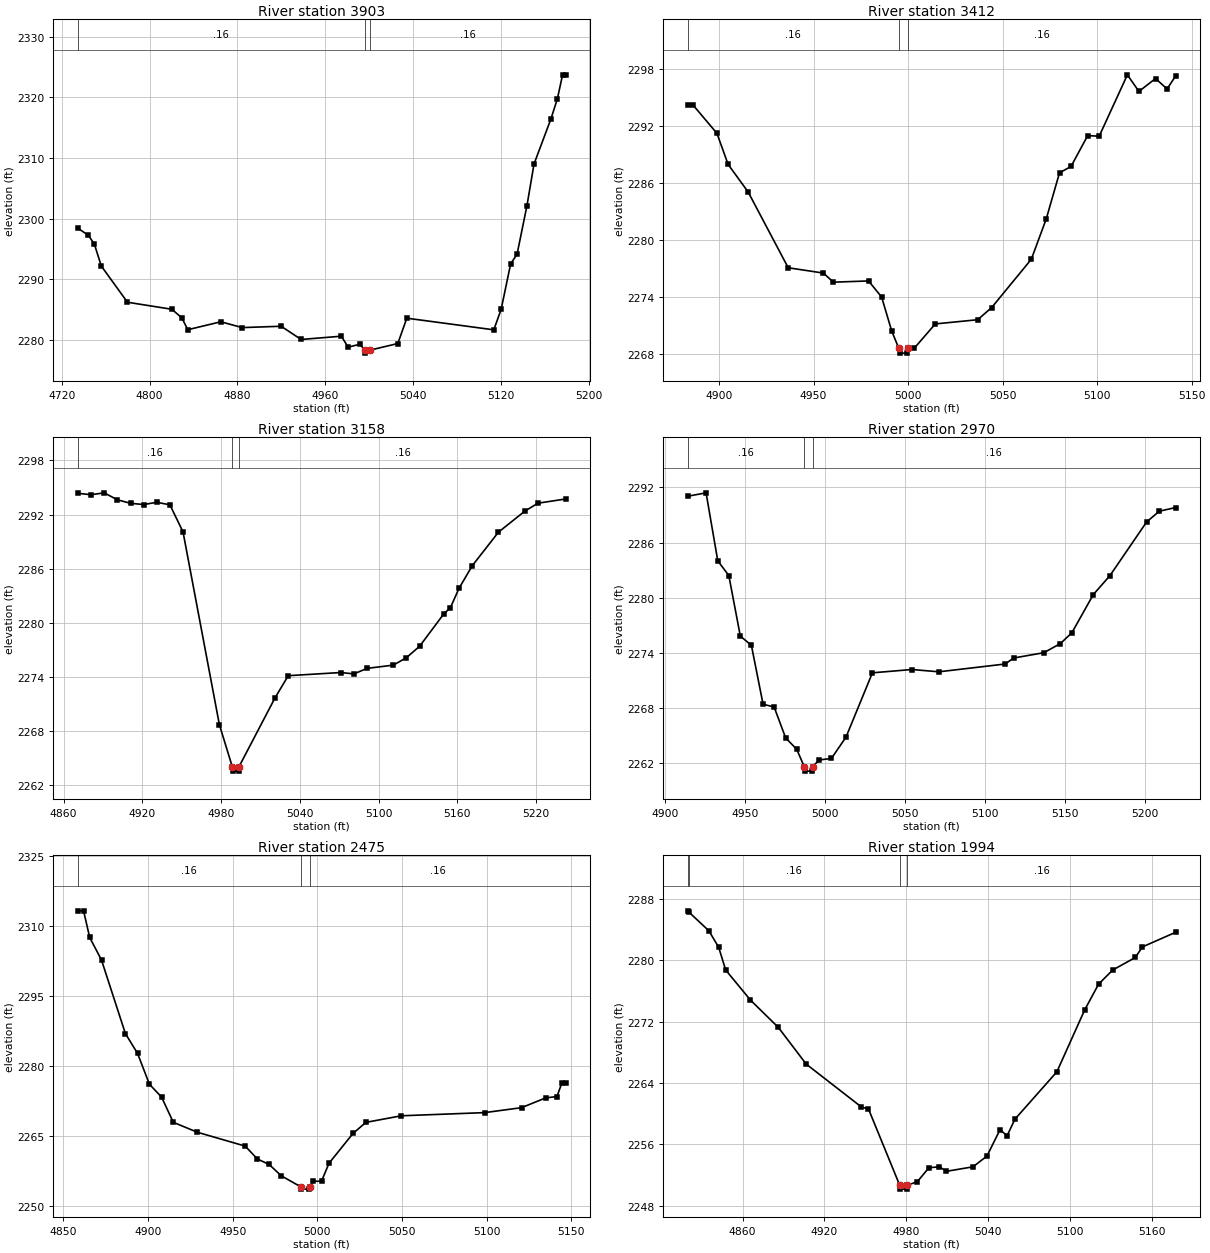
Type RM Length L Ch R = 1,3903,491,491,491
BEGIN DESCRIPTION:
232
END DESCRIPTION:
XS GIS Cut Line= 3
      1487655.01      6786088.03      1487560.69      6785840.06
      1487654.98      6785688.03
#Sta/Elev= 30
  4734.7 2298.44  4744.4 2297.25  4749.8 2295.79  4756.1 2292.19  4779.9 2286.23
  4820.3 2285.07  4829.4 2283.66  4834.8 2281.70  4864.9 2283.01  4884.3 2282.05
  4919.8 2282.27  4938.0 2280.09  4974.6 2280.63  4980.8 2278.83  4991.5 2279.30
  4996.0 2278.34  4996.4 2277.84  5000.8 2278.34  5026.0 2279.42  5034.2 2283.60
  5113.4 2281.68  5120.1 2285.07  5128.7 2292.53  5134.6 2294.17  5143.6 2302.17
  5150.0 2309.01  5165.4 2316.45  5171.3 2319.79  5176.0 2323.72  5178.9 2323.72
#Mann=3,-1,0
  4734.7    0.16       0  4996.0    0.07       0  5000.8    0.16       0
Bank Sta=4996,5000.8
Exp/Cntr=0.3,0.1

Type RM Length L Ch R = 1,3412,254,254,254
BEGIN DESCRIPTION:
231
END DESCRIPTION:
XS GIS Cut Line= 3
      1487854.99      6786138.04      1487894.20      6786028.33
      1487974.17      6785911.48
#Sta/Elev= 30
  4883.5 2294.22  4886.2 2294.22  4898.9 2291.22  4904.8 2287.95  4915.4 2285.04
  4936.6 2277.05  4955.2 2276.49  4960.5 2275.53  4979.1 2275.66  4986.0 2273.97
  4991.3 2270.41  4995.1 2268.55  4995.5 2268.05  4999.6 2268.05  4999.9 2268.55
  5003.2 2268.55  5014.4 2271.13  5036.8 2271.57  5044.2 2272.85  5065.2 2277.95
  5073.1 2282.21  5080.1 2287.06  5086.2 2287.73  5095.0 2290.98  5101.1 2290.92
  5116.0 2297.39  5122.1 2295.64  5130.9 2297.00  5137.0 2295.90  5141.6 2297.29
#Mann=3,-1,0
  4883.5    0.16       0  4995.1    0.07       0  4999.9    0.16       0
Bank Sta=4995.1,4999.9
Exp/Cntr=0.3,0.1

Type RM Length L Ch R = 1,3158,188,188,188
BEGIN DESCRIPTION:
838
END DESCRIPTION:
XS GIS Cut Line= 2
      1488053.57      6786318.08      1488075.20      6785946.81
#Sta/Elev= 30
  4870.8 2294.36  4880.9 2294.20  4890.9 2294.41  4900.9 2293.64  4911.0 2293.25
  4921.0 2293.11  4931.0 2293.36  4941.0 2293.08  4951.0 2290.07  4978.7 2268.71
  4988.5 2264.06  4988.9 2263.56  4993.3 2263.56  4993.7 2264.06  5021.1 2271.68
  5031.2 2274.14  5071.2 2274.49  5081.2 2274.34  5091.3 2274.95  5111.3 2275.31
  5121.3 2276.14  5131.3 2277.40  5149.8 2281.00  5154.8 2281.68  5161.4 2283.84
  5171.4 2286.32  5191.4 2290.05  5211.5 2292.38  5221.5 2293.26  5242.7 2293.73
#Mann=3,-1,0
  4870.8    0.16       0  4988.5    0.07       0  4993.7    0.16       0
Bank Sta=4988.5,4993.7
Exp/Cntr=0.3,0.1

Type RM Length L Ch R = 1,2970,495,495,495
BEGIN DESCRIPTION:
230
END DESCRIPTION:
XS GIS Cut Line= 3
      1488266.51      6786262.70      1488207.28      6786200.63
      1488154.99      6785987.96
#Sta/Elev= 30
  4914.2 2291.05  4925.6 2291.42  4932.9 2284.02  4939.8 2282.42  4947.0 2275.82
  4953.9 2274.83  4961.2 2268.41  4968.1 2268.11  4975.3 2264.75  4982.2 2263.51
  4986.9 2261.63  4987.3 2261.13  4991.7 2261.13  4992.1 2261.63  4996.4 2262.35
  5003.9 2262.51  5013.0 2264.83  5029.5 2271.83  5054.2 2272.19  5071.0 2271.94
  5112.5 2272.79  5117.7 2273.44  5136.6 2274.02  5146.9 2275.01  5154.1 2276.19
  5167.5 2280.35  5177.8 2282.39  5200.8 2288.25  5208.7 2289.42  5219.0 2289.82
#Mann=3,-1,0
  4914.2    0.16       0  4986.9    0.07       0  4992.1    0.16       0
Bank Sta=4986.9,4992.1
Exp/Cntr=0.3,0.1

Type RM Length L Ch R = 1,2475,481,481,481
BEGIN DESCRIPTION:
229
END DESCRIPTION:
XS GIS Cut Line= 3
      1488654.97      6785987.97      1488556.56      6785886.29
      1488446.33      6785789.35
#Sta/Elev= 30
  4858.5 2313.21  4861.9 2313.21  4865.5 2307.53  4872.5 2302.67  4886.6 2286.94
  4893.8 2282.69  4900.8 2276.09  4908.0 2273.33  4914.9 2267.94  4929.1 2265.81
  4957.4 2262.84  4964.6 2260.08  4971.5 2258.92  4978.7 2256.49  4990.2 2254.13
  4990.6 2253.63  4995.1 2253.63  4995.5 2254.13  4997.5 2255.32  5002.5 2255.32
  5006.9 2259.16  5021.1 2265.55  5028.7 2267.92  5049.6 2269.33  5098.9 2270.01
  5120.7 2271.07  5134.9 2273.16  5141.6 2273.45  5144.4 2276.26  5146.8 2276.26
#Mann=3,-1,0
  4858.5    0.16       0  4990.2    0.07       0  4995.5    0.16       0
Bank Sta=4990.2,4995.5
Exp/Cntr=0.3,0.1

Type RM Length L Ch R = 1,1994,484,484,484
BEGIN DESCRIPTION:
228
END DESCRIPTION:
XS GIS Cut Line= 3
      1488890.14      6785527.62      1488713.19      6785494.08
      1488539.79      6785457.09
#Sta/Elev= 30
  4819.9 2286.45  4820.4 2286.33  4835.3 2283.85  4842.5 2281.70  4847.6 2278.74
  4865.8 2274.81  4886.2 2271.25  4906.6 2266.47  4947.1 2260.87  4952.2 2260.63
  4975.1 2250.67  4975.6 2250.17  4980.1 2250.17  4980.5 2250.67  4988.0 2251.14
  4996.5 2252.96  5004.2 2253.08  5009.3 2252.49  5028.8 2253.08  5039.0 2254.48
  5048.6 2257.93  5053.7 2257.11  5059.5 2259.29  5090.2 2265.46  5110.6 2273.54
  5120.8 2276.90  5131.1 2278.73  5147.7 2280.37  5152.8 2281.74  5177.3 2283.66
#Mann=4,-1,0
  4819.9    0.07       0  4820.4    0.16       0  4975.1    0.07       0
  4980.5    0.16       0
Bank Sta=4975.1,4980.5
Exp/Cntr=0.3,0.1

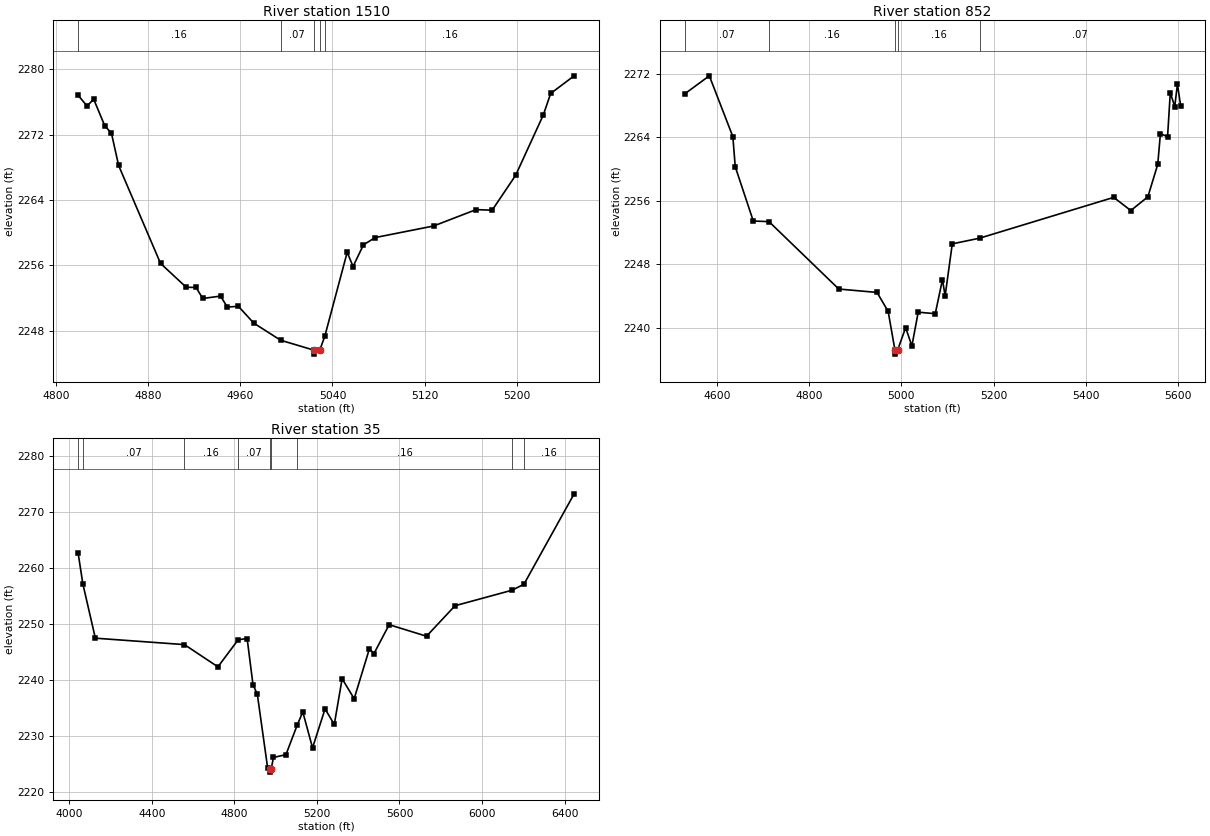
Type RM Length L Ch R = 1,1510,658,658,658
BEGIN DESCRIPTION:
227
END DESCRIPTION:
XS GIS Cut Line= 3
      1488955.01      6785138.00      1488800.85      6785043.35
      1488554.97      6785088.01
#Sta/Elev= 30
  4819.1 2276.80  4826.8 2275.50  4832.7 2276.30  4842.2 2273.09  4848.1 2272.14
  4854.3 2268.21  4890.7 2256.23  4913.0 2253.31  4921.5 2253.29  4927.4 2251.94
  4942.8 2252.23  4948.7 2250.89  4958.3 2250.98  4971.7 2248.92  4995.0 2246.83
  5023.6 2245.63  5024.0 2245.13  5029.0 2245.63  5033.3 2247.29  5052.8 2257.59
  5057.9 2255.85  5066.9 2258.50  5077.1 2259.39  5127.9 2260.81  5164.7 2262.81
  5178.7 2262.74  5199.1 2267.01  5223.2 2274.42  5229.5 2277.02  5249.9 2279.18
#Mann=5,-1,0
  4819.1    0.16       0  4995.0    0.07       0  5023.6    0.07       0
  5029.0    0.07       0  5033.3    0.16       0
Bank Sta=5023.6,5029
Exp/Cntr=0.3,0.1

Type RM Length L Ch R = 1,852,817,817,817
BEGIN DESCRIPTION:
766
END DESCRIPTION:
XS GIS Cut Line= 3
      1489406.69      6784562.63      1488956.11      6784435.20
      1488434.91      6784747.00
#Sta/Elev= 30
  4529.9 2269.47  4583.6 2271.76  4634.6 2264.09  4639.8 2260.30  4678.9 2253.45
  4713.0 2253.37  4864.3 2244.87  4947.3 2244.44  4971.4 2242.04  4986.1 2237.16
  4986.5 2236.66  4991.8 2237.16  5009.3 2240.00  5022.8 2237.69  5036.5 2241.95
  5073.5 2241.76  5089.1 2246.05  5094.9 2244.01  5110.4 2250.57  5169.5 2251.28
  5460.5 2256.43  5497.5 2254.77  5534.5 2256.50  5555.9 2260.59  5561.7 2264.47
  5577.2 2264.08  5583.1 2269.63  5592.8 2267.89  5598.6 2270.71  5605.5 2268.01
#Mann=5,-1,0
  4529.9    0.07       0  4713.0    0.16       0  4986.1    0.07       0
  4991.8    0.16       0  5169.5    0.07       0
Bank Sta=4986.1,4991.8
Exp/Cntr=0.3,0.1

Type RM Length L Ch R = 1,35,0,0,0
BEGIN DESCRIPTION:
226
END DESCRIPTION:
XS GIS Cut Line= 4
      1489609.31      6784471.64      1488956.11      6783772.92
      1488680.46      6783890.39      1488093.54      6784876.74
#Sta/Elev= 30
  4042.6 2262.75  4065.7 2257.21  4126.2 2247.51  4558.1 2246.36  4720.2 2242.39
  4818.4 2247.23  4861.8 2247.45  4890.2 2239.20  4911.2 2237.49  4961.0 2224.37
  4972.3 2224.08  4972.8 2223.58  4978.0 2224.08  4989.3 2226.20  5049.8 2226.70
  5104.0 2231.94  5131.5 2234.33  5178.8 2227.92  5239.4 2234.88  5284.1 2232.09
  5322.1 2240.26  5380.5 2236.70  5454.6 2245.65  5476.0 2244.73  5550.0 2249.92
  5731.1 2247.86  5869.3 2253.31  6144.8 2256.07  6203.1 2257.14  6446.5 2273.30
#Mann=9,-1,0
  4042.6    0.16       0  4065.7    0.07       0  4558.1    0.16       0
  4818.4    0.07       0  4972.3    0.07       0  4978.0    0.07       0
  5104.0    0.16       0  6144.8    0.07       0  6203.1    0.16       0
Bank Sta=4972.3,4978
Exp/Cntr=0.3,0.1

Chan Stop Cuts=-1