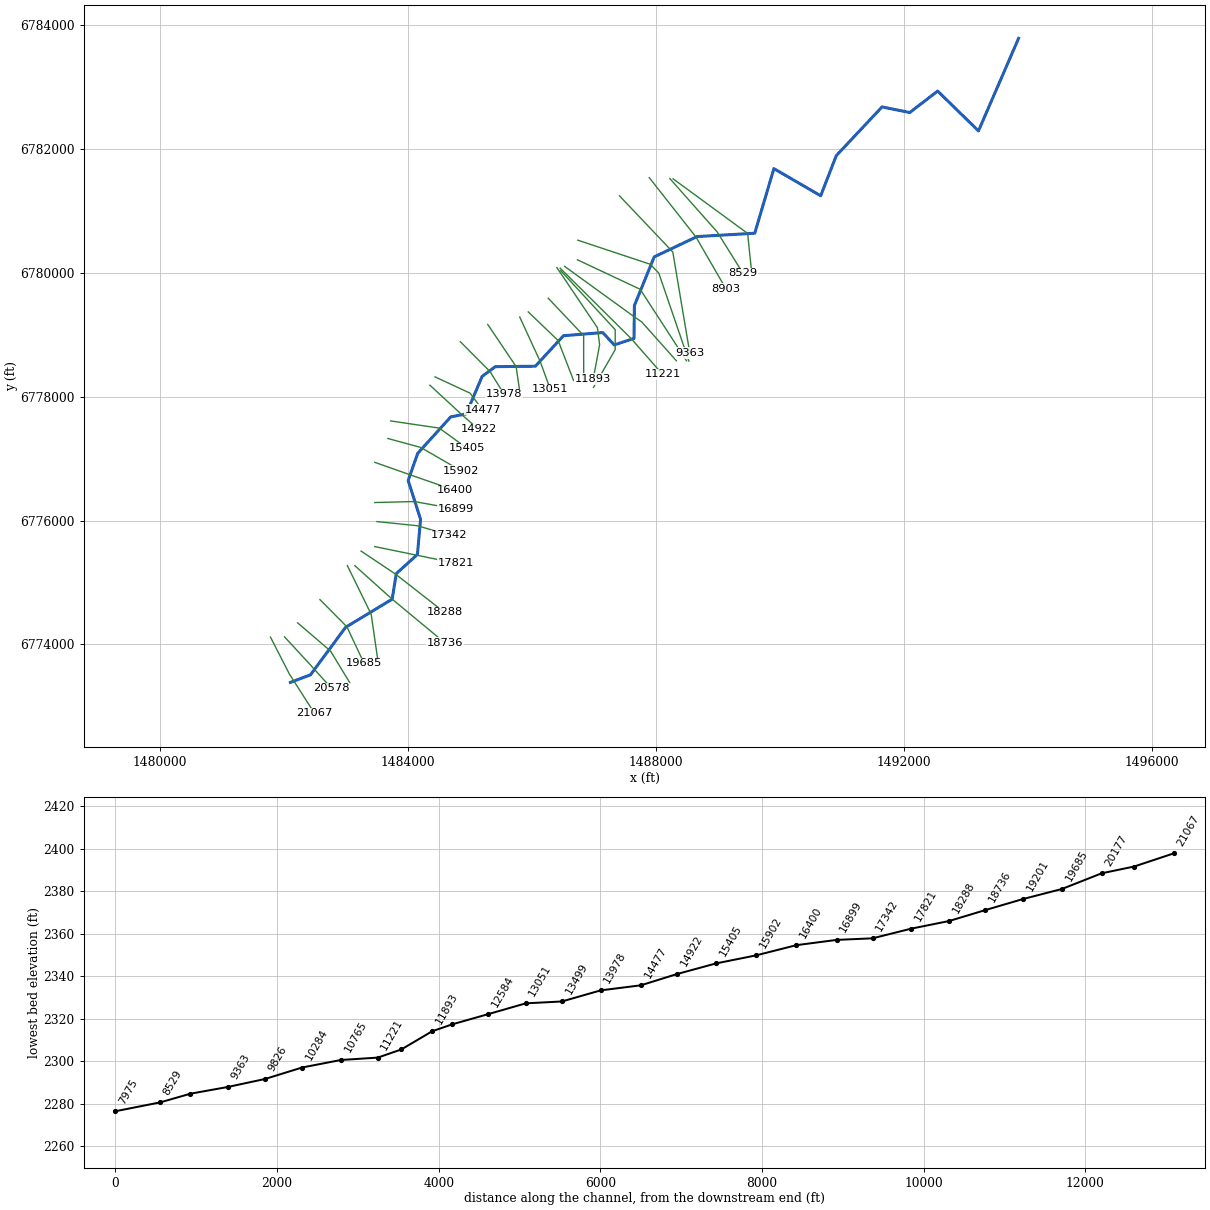
--- Elm 18.prj (project) ---

Proj Title=Elm 18 Base Level Engineering
Current Plan=p01
Default Exp/Contr=0.3,0.1
English Units
Geom File=g01
Flow File=f01
Plan File=p01
BEGIN DESCRIPTION:
Elm 18
END DESCRIPTION:

--- Elm 18.p01 (plan) ---

Plan Title=Multiple Run
Short Identifier=Multiple
Geom File=g01
Flow File=f01
Subcritical Flow
K Sum by GR= 0
Std Step Tol= 0.01
Critical Tol= 0.01
Num of Std Step Trials= 20
Max Error Tol= 0.3
Flow Tol Ratio= 0.001
Split Flow NTrial= 30
Split Flow Tol= 0.02
Split Flow Ratio= 0.02
Log Output Level= 0
Friction Slope Method= 1
Unsteady Friction Slope Method= 2
Unsteady Bridges Friction Slope Method= 1
Parabolic Critical Depth
Global Vel Dist=  1 , 1 , 1
Global Log Level= 0
CheckData=True
Encroach Param= -1, 0, 0, 0
BEGIN DESCRIPTION:
Multiple Run
END DESCRIPTION:

--- Elm 18.f01 (steady flow) ---

Flow Title=Multiple
Number of Profiles=7
Profile Names=10-year,25-year,50-year,1pct_min,100-year,1pct_plu,500-year
River Rch & RM= Elm 18,Reach-1,21067
     262     365     451     345     553     760     840
River Rch & RM= Elm 18,Reach-1,18736
     546     793    1010     789    1260    1740    2020
River Rch & RM= Elm 18,Reach-1,11221
     845    1250    1610    1280    2060    2830    3380
River Rch & RM= Elm 18,Reach-1,6644
     941    1400    1810    1440    2310    3180    3820
Boundary for River Rch & Prof#=Elm 18,Reach-1,1
Up Type=0
Dn Type=3
Dn Slope=0.005
Boundary for River Rch & Prof#=Elm 18,Reach-1,2
Up Type=0
Dn Type=3
Dn Slope=0.005
Boundary for River Rch & Prof#=Elm 18,Reach-1,3
Up Type=0
Dn Type=3
Dn Slope=0.005
Boundary for River Rch & Prof#=Elm 18,Reach-1,4
Up Type=0
Dn Type=3
Dn Slope=0.005
Boundary for River Rch & Prof#=Elm 18,Reach-1,5
Up Type=0
Dn Type=3
Dn Slope=0.005
Boundary for River Rch & Prof#=Elm 18,Reach-1,6
Up Type=0
Dn Type=3
Dn Slope=0.005
Boundary for River Rch & Prof#=Elm 18,Reach-1,7
Up Type=0
Dn Type=3
Dn Slope=0.005

--- Elm 18.g01 (geometry) ---

Geom Title=Existing Conditions

River Reach=Elm 18,Reach-1
Reach XY= 30
      1482105.00      6773388.00      1482429.01      6773510.66
      1482995.19      6774277.49      1483746.86      6774731.94
      1483813.14      6775144.06      1484154.34      6775453.83
      1484205.04      6776022.66      1484004.54      6776648.19
      1484158.75      6777086.45      1484691.33      6777674.77
      1484941.54      6777724.37      1485198.93      6778329.85
      1485411.05      6778486.34      1486057.43      6778493.52
      1486510.85      6778985.94      1487144.71      6779037.03
      1487329.96      6778837.50      1487649.68      6778942.92
      1487655.52      6779472.78      1487974.62      6780258.48
      1488665.50      6780586.80      1489597.38      6780641.07
      1489906.49      6781684.55      1490661.50      6781245.62
      1490913.13      6781894.07      1491651.66      6782680.40
      1492099.07      6782590.24      1492549.13      6782936.50
      1493207.43      6782293.40      1493855.00      6783788.00

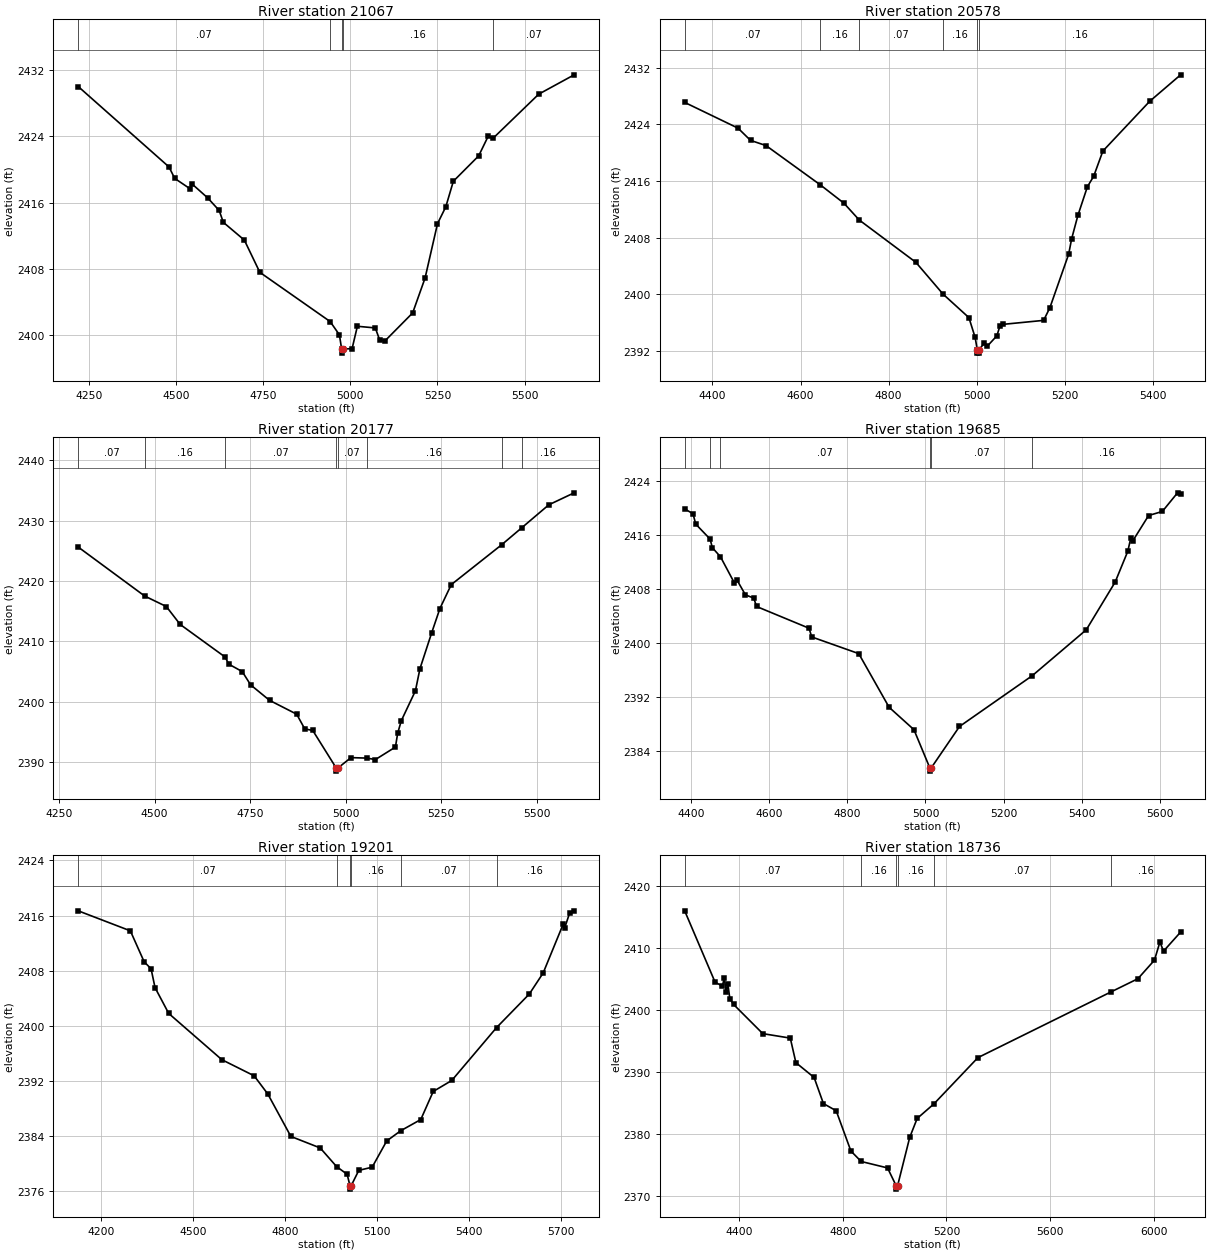
Type RM Length L Ch R = 1,21067,489,489,489
BEGIN DESCRIPTION:
elmc289
END DESCRIPTION:
XS GIS Cut Line= 3
      1481783.32      6774118.86      1482091.10      6773517.72
      1482495.05      6772887.76
#Sta/Elev= 30
  4218.6 2430.01  4479.1 2420.31  4495.7 2418.92  4540.1 2417.66  4545.7 2418.24
  4590.3 2416.57  4623.3 2415.05  4635.2 2413.62  4695.5 2411.48  4740.0 2407.59
  4941.8 2401.65  4968.4 2400.05  4974.8 2398.34  4975.0 2397.84  4978.8 2398.34
  5004.8 2398.38  5020.0 2401.08  5071.5 2400.88  5083.7 2399.46  5098.6 2399.29
  5178.7 2402.69  5214.4 2406.91  5250.0 2413.46  5273.8 2415.49  5295.5 2418.58
  5368.2 2421.64  5395.3 2423.99  5409.4 2423.76  5540.7 2429.09  5642.3 2431.42
#Mann=5,-1,0
  4218.6    0.07       0  4941.8    0.16       0  4974.8    0.07       0
  4978.8    0.16       0  5409.4    0.07       0
Bank Sta=4974.8,4978.8
Exp/Cntr=0.3,0.1

Type RM Length L Ch R = 1,20578,401,401,401
BEGIN DESCRIPTION:
elmc34
END DESCRIPTION:
XS GIS Cut Line= 3
      1482009.35      6774123.63      1482413.30      6773686.03
      1482768.55      6773292.37
#Sta/Elev= 30
  4337.0 2427.11  4458.1 2423.47  4486.5 2421.74  4521.6 2421.01  4644.5 2415.47
  4698.5 2412.86  4733.3 2410.48  4861.8 2404.50  4923.4 2400.01  4982.2 2396.68
  4996.4 2393.87  5001.1 2392.16  5001.4 2391.66  5004.9 2391.66  5005.1 2392.16
  5017.3 2393.06  5024.2 2392.66  5045.7 2394.11  5052.4 2395.45  5059.9 2395.73
  5151.8 2396.29  5166.0 2398.08  5208.6 2405.64  5215.4 2407.82  5229.6 2411.13
  5251.2 2415.19  5265.4 2416.66  5286.3 2420.23  5392.5 2427.26  5462.8 2431.01
#Mann=6,-1,0
  4337.0    0.07       0  4644.5    0.16       0  4733.3    0.07       0
  4923.4    0.16       0  5001.1    0.07       0  5005.1    0.16       0
Bank Sta=5001.1,5005.1
Exp/Cntr=0.3,0.1

Type RM Length L Ch R = 1,20177,492,492,492
BEGIN DESCRIPTION:
elmc33
END DESCRIPTION:
XS GIS Cut Line= 3
      1482220.92      6774349.66      1482752.47      6773894.04
      1483062.51      6773383.04
#Sta/Elev= 30
  4299.9 2425.63  4473.8 2417.51  4530.5 2415.77  4566.7 2412.80  4684.2 2407.40
  4694.1 2406.21  4729.2 2404.98  4751.1 2402.78  4800.5 2400.22  4871.6 2397.92
  4892.7 2395.48  4913.6 2395.23  4975.2 2388.98  4975.5 2388.48  4979.2 2388.98
  5013.7 2390.72  5054.7 2390.64  5077.7 2390.40  5130.0 2392.47  5135.9 2394.77
  5145.5 2396.86  5182.3 2401.79  5194.2 2405.47  5225.0 2411.44  5246.4 2415.44
  5276.1 2419.40  5408.0 2426.01  5460.5 2428.82  5531.3 2432.63  5597.7 2434.62
#Mann=8,-1,0
  4299.9    0.07       0  4473.8    0.16       0  4684.2    0.07       0
  4975.2    0.07       0  4979.2    0.07       0  5054.7    0.16       0
  5408.0    0.07       0  5460.5    0.16       0
Bank Sta=4975.2,4979.2
Exp/Cntr=0.3,0.1

Type RM Length L Ch R = 1,19685,484,484,484
BEGIN DESCRIPTION:
elmc32
END DESCRIPTION:
XS GIS Cut Line= 3
      1482581.63      6774724.70      1483015.48      6774286.84
      1483293.30      6773695.66
#Sta/Elev= 30
  4383.6 2419.81  4404.9 2419.09  4411.9 2417.56  4448.7 2415.35  4454.4 2414.08
  4475.2 2412.74  4510.9 2408.87  4518.0 2409.25  4539.2 2407.11  4560.5 2406.64
  4567.5 2405.40  4701.9 2402.19  4708.9 2400.90  4829.2 2398.44  4906.9 2390.52
  4970.5 2387.21  5011.0 2381.59  5011.2 2381.09  5015.0 2381.59  5087.1 2387.68
  5273.6 2395.19  5411.7 2401.96  5485.6 2409.00  5518.0 2413.56  5525.7 2415.52
  5531.2 2415.13  5571.3 2418.83  5606.4 2419.43  5645.3 2422.18  5653.2 2421.96
#Mann=6,-1,0
  4383.6    0.07       0  4448.7    0.16       0  4475.2    0.07       0
  5011.0    0.07       0  5015.0    0.07       0  5273.6    0.16       0
Bank Sta=5011,5015
Exp/Cntr=0.3,0.1

Type RM Length L Ch R = 1,19201,465,465,465
BEGIN DESCRIPTION:
elmc31
END DESCRIPTION:
XS GIS Cut Line= 3
      1483024.02      6775272.93      1483408.23      6774488.25
      1483514.51      6773753.39
#Sta/Elev= 30
  4126.3 2416.68  4296.2 2413.78  4341.2 2409.29  4363.7 2408.28  4376.7 2405.54
  4421.3 2401.80  4594.3 2395.10  4699.6 2392.76  4744.2 2390.12  4819.3 2383.97
  4914.9 2382.30  4968.3 2379.60  5002.7 2378.48  5011.9 2376.83  5012.1 2376.33
  5015.9 2376.83  5040.7 2379.05  5084.2 2379.51  5131.6 2383.31  5177.1 2384.79
  5242.7 2386.42  5283.2 2390.49  5343.8 2392.09  5489.6 2399.75  5596.4 2404.62
  5641.5 2407.67  5706.7 2414.74  5711.8 2414.22  5727.7 2416.36  5742.5 2416.59
#Mann=6,-1,0
  4126.3    0.07       0  4968.3    0.16       0  5011.9    0.07       0
  5015.9    0.16       0  5177.1    0.07       0  5489.6    0.16       0
Bank Sta=5011.9,5015.9
Exp/Cntr=0.3,0.1

Type RM Length L Ch R = 1,18736,448,448,448
BEGIN DESCRIPTION:
elmc30
END DESCRIPTION:
XS GIS Cut Line= 3
      1483144.26      6775272.91      1483746.86      6774731.94
      1484596.49      6774027.46
#Sta/Elev= 30
  4190.2 2416.03  4307.6 2404.51  4336.0 2403.89  4342.7 2405.23  4350.2 2403.01
  4357.0 2404.18  4364.4 2401.87  4378.6 2400.94  4491.5 2396.22  4597.7 2395.50
  4619.3 2391.54  4689.6 2389.15  4725.5 2384.94  4774.8 2383.78  4831.6 2377.28
  4871.2 2375.60  4972.9 2374.56  5006.7 2371.64  5007.0 2371.14  5011.4 2371.64
  5058.5 2379.49  5087.2 2382.54  5151.6 2384.88  5321.6 2392.35  5833.6 2402.92
  5938.9 2405.08  6002.7 2408.07  6023.8 2410.99  6037.8 2409.53  6103.7 2412.60
#Mann=6,-1,0
  4190.2    0.07       0  4871.2    0.16       0  5006.7    0.07       0
  5011.4    0.16       0  5151.6    0.07       0  5833.6    0.16       0
Bank Sta=5006.7,5011.4
Exp/Cntr=0.3,0.1

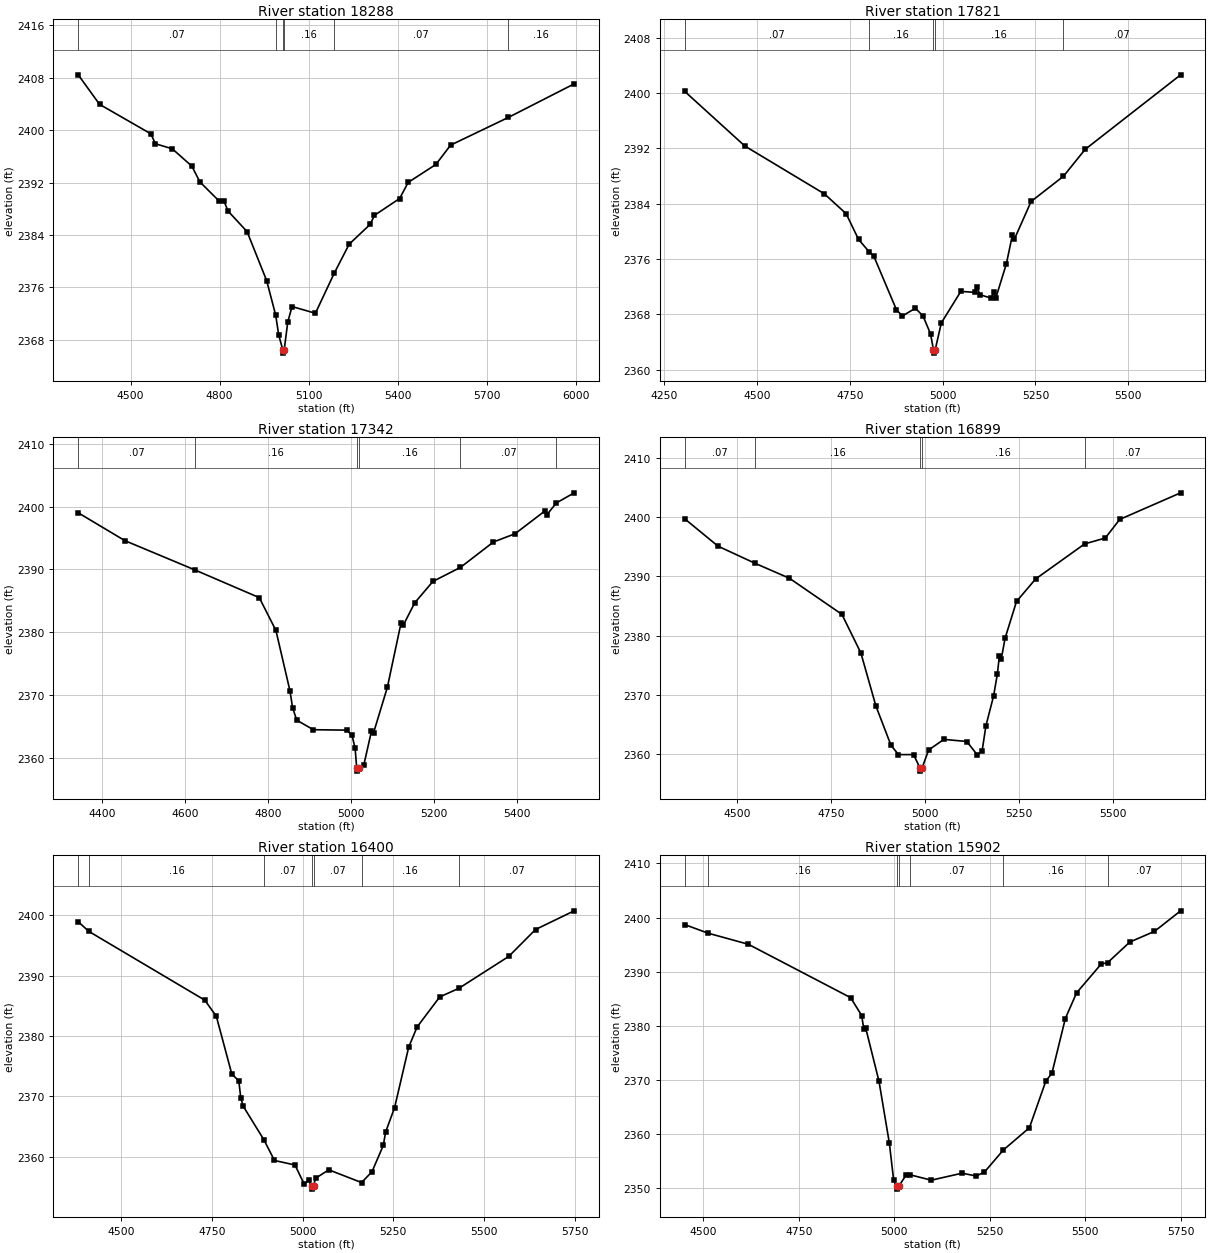
Type RM Length L Ch R = 1,18288,467,467,467
BEGIN DESCRIPTION:
elmc29
END DESCRIPTION:
XS GIS Cut Line= 3
      1483245.26      6775508.54      1483807.49      6775131.97
      1484590.84      6774518.62
#Sta/Elev= 30
  4323.3 2408.43  4395.2 2403.93  4568.3 2399.43  4583.3 2397.92  4640.3 2397.15
  4706.4 2394.50  4733.4 2392.10  4799.4 2389.13  4814.4 2389.20  4828.5 2387.64
  4892.5 2384.52  4958.5 2377.04  4988.9 2371.78  4999.1 2368.75  5012.9 2366.49
  5013.2 2365.99  5017.6 2366.49  5029.7 2370.76  5044.1 2373.09  5122.8 2372.07
  5186.1 2378.17  5236.7 2382.61  5307.3 2385.62  5321.7 2387.00  5406.7 2389.57
  5435.6 2392.03  5528.8 2394.76  5578.5 2397.71  5773.0 2401.93  5994.9 2407.05
#Mann=6,-1,0
  4323.3    0.07       0  4988.9    0.16       0  5012.9    0.07       0
  5017.6    0.16       0  5186.1    0.07       0  5773.0    0.16       0
Bank Sta=5012.9,5017.6
Exp/Cntr=0.3,0.1

Type RM Length L Ch R = 1,17821,479,479,479
BEGIN DESCRIPTION:
elmc28
END DESCRIPTION:
XS GIS Cut Line= 3
      1483466.41      6775580.70      1484146.89      6775441.39
      1484774.47      6775311.40
#Sta/Elev= 30
  4305.4 2400.26  4467.3 2392.36  4681.6 2385.44  4740.2 2382.57  4773.5 2378.86
  4801.7 2377.09  4814.3 2376.48  4875.6 2368.69  4891.6 2367.78  4926.6 2368.90
  4947.1 2367.79  4967.4 2365.21  4975.3 2362.91  4975.6 2362.41  4980.1 2362.91
  4996.5 2366.78  5049.1 2371.34  5087.8 2371.19  5092.9 2371.96  5100.2 2370.87
  5130.8 2370.35  5137.9 2371.31  5143.0 2370.34  5171.7 2375.33  5188.1 2379.53
  5193.2 2378.88  5238.3 2384.34  5325.5 2387.99  5383.8 2391.87  5640.9 2402.65
#Mann=5,-1,0
  4305.4    0.07       0  4801.7    0.16       0  4975.3    0.07       0
  4980.1    0.16       0  5325.5    0.07       0
Bank Sta=4975.3,4980.1
Exp/Cntr=0.3,0.1

Type RM Length L Ch R = 1,17342,443,443,443
BEGIN DESCRIPTION:
elmc27
END DESCRIPTION:
XS GIS Cut Line= 3
      1483500.07      6775984.64      1484155.09      6775917.97
      1484671.71      6775763.95
#Sta/Elev= 30
  4341.6 2399.01  4454.3 2394.57  4622.5 2389.93  4778.8 2385.49  4819.0 2380.26
  4852.9 2370.64  4859.2 2367.98  4869.2 2365.97  4909.4 2364.45  4989.9 2364.38
  5002.6 2363.57  5010.3 2361.47  5014.0 2358.35  5014.3 2357.85  5019.0 2358.35
  5031.2 2358.82  5049.6 2364.19  5054.9 2363.99  5088.0 2371.19  5121.2 2381.49
  5126.4 2381.09  5154.3 2384.68  5198.2 2388.08  5264.6 2390.31  5344.3 2394.36
  5396.4 2395.67  5468.3 2399.29  5473.6 2398.73  5496.1 2400.57  5539.1 2402.19
#Mann=6,-1,0
  4341.6    0.07       0  4622.5    0.16       0  5014.0    0.07       0
  5019.0    0.16       0  5264.6    0.07       0  5496.1    0.16       0
Bank Sta=5014,5019
Exp/Cntr=0.3,0.1

Type RM Length L Ch R = 1,16899,499,499,499
BEGIN DESCRIPTION:
elmc26
END DESCRIPTION:
XS GIS Cut Line= 3
      1483466.43      6776292.41      1484105.53      6776308.43
      1484774.43      6776186.61
#Sta/Elev= 30
  4360.7 2399.70  4449.3 2395.08  4548.8 2392.16  4639.4 2389.66  4778.9 2383.57
  4829.4 2377.05  4869.4 2368.09  4909.4 2361.48  4929.4 2359.90  4969.5 2359.90
  4986.9 2357.61  4987.3 2357.11  4992.0 2357.61  5009.6 2360.68  5050.3 2362.47
  5111.3 2362.11  5139.3 2359.82  5151.9 2360.53  5162.1 2364.79  5182.4 2369.79
  5192.6 2373.55  5197.7 2376.54  5202.8 2376.01  5212.9 2379.53  5243.4 2385.75
  5294.2 2389.54  5424.6 2395.46  5479.5 2396.45  5517.9 2399.59  5679.9 2404.08
#Mann=5,-1,0
  4360.7    0.07       0  4548.8    0.16       0  4986.9    0.07       0
  4992.0    0.16       0  5424.6    0.07       0
Bank Sta=4986.9,4992
Exp/Cntr=0.3,0.1

Type RM Length L Ch R = 1,16400,498,498,498
BEGIN DESCRIPTION:
elmc25
END DESCRIPTION:
XS GIS Cut Line= 3
      1483466.44      6776941.59      1484048.86      6776735.83
      1484755.16      6776489.58
#Sta/Elev= 30
  4382.3 2398.94  4411.6 2397.34  4730.8 2385.95  4762.6 2383.28  4805.0 2373.75
  4824.6 2372.55  4829.9 2369.74  4836.8 2368.36  4893.7 2362.80  4922.7 2359.38
  4979.2 2358.63  5004.9 2355.42  5017.1 2356.15  5025.1 2355.13  5025.5 2354.63
  5030.3 2355.13  5036.0 2356.43  5072.3 2357.83  5162.5 2355.72  5191.3 2357.51
  5222.4 2361.87  5228.9 2364.11  5253.5 2368.13  5292.4 2378.17  5315.6 2381.51
  5377.8 2386.48  5430.3 2387.90  5567.8 2393.19  5641.6 2397.65  5748.0 2400.75
#Mann=7,-1,0
  4382.3    0.07       0  4411.6    0.16       0  4893.7    0.07       0
  5025.1    0.07       0  5030.3    0.07       0  5162.5    0.16       0
  5430.3    0.07       0
Bank Sta=5025.1,5030.3
Exp/Cntr=0.3,0.1

Type RM Length L Ch R = 1,15902,497,497,497
BEGIN DESCRIPTION:
elmc24
END DESCRIPTION:
XS GIS Cut Line= 3
      1483677.98      6777326.31      1484207.41      6777182.17
      1484856.21      6776806.93
#Sta/Elev= 30
  4451.3 2398.70  4512.6 2397.11  4617.7 2395.07  4885.7 2385.20  4914.6 2381.90
  4920.2 2379.39  4925.4 2379.52  4960.0 2369.74  4987.1 2358.31  4998.4 2351.43
  5006.2 2350.33  5006.6 2349.83  5011.4 2350.33  5031.9 2352.53  5042.4 2352.46
  5096.8 2351.48  5177.2 2352.77  5214.5 2352.26  5236.0 2352.98  5285.5 2357.06
  5353.7 2361.17  5396.8 2369.82  5412.6 2371.23  5447.7 2381.34  5477.2 2386.09
  5541.8 2391.43  5558.4 2391.66  5616.4 2395.47  5681.0 2397.44  5749.5 2401.24
#Mann=7,-1,0
  4451.3    0.07       0  4512.6    0.16       0  5006.2    0.07       0
  5011.4    0.16       0  5042.4    0.07       0  5285.5    0.16       0
  5558.4    0.07       0
Bank Sta=5006.2,5011.4
Exp/Cntr=0.3,0.1

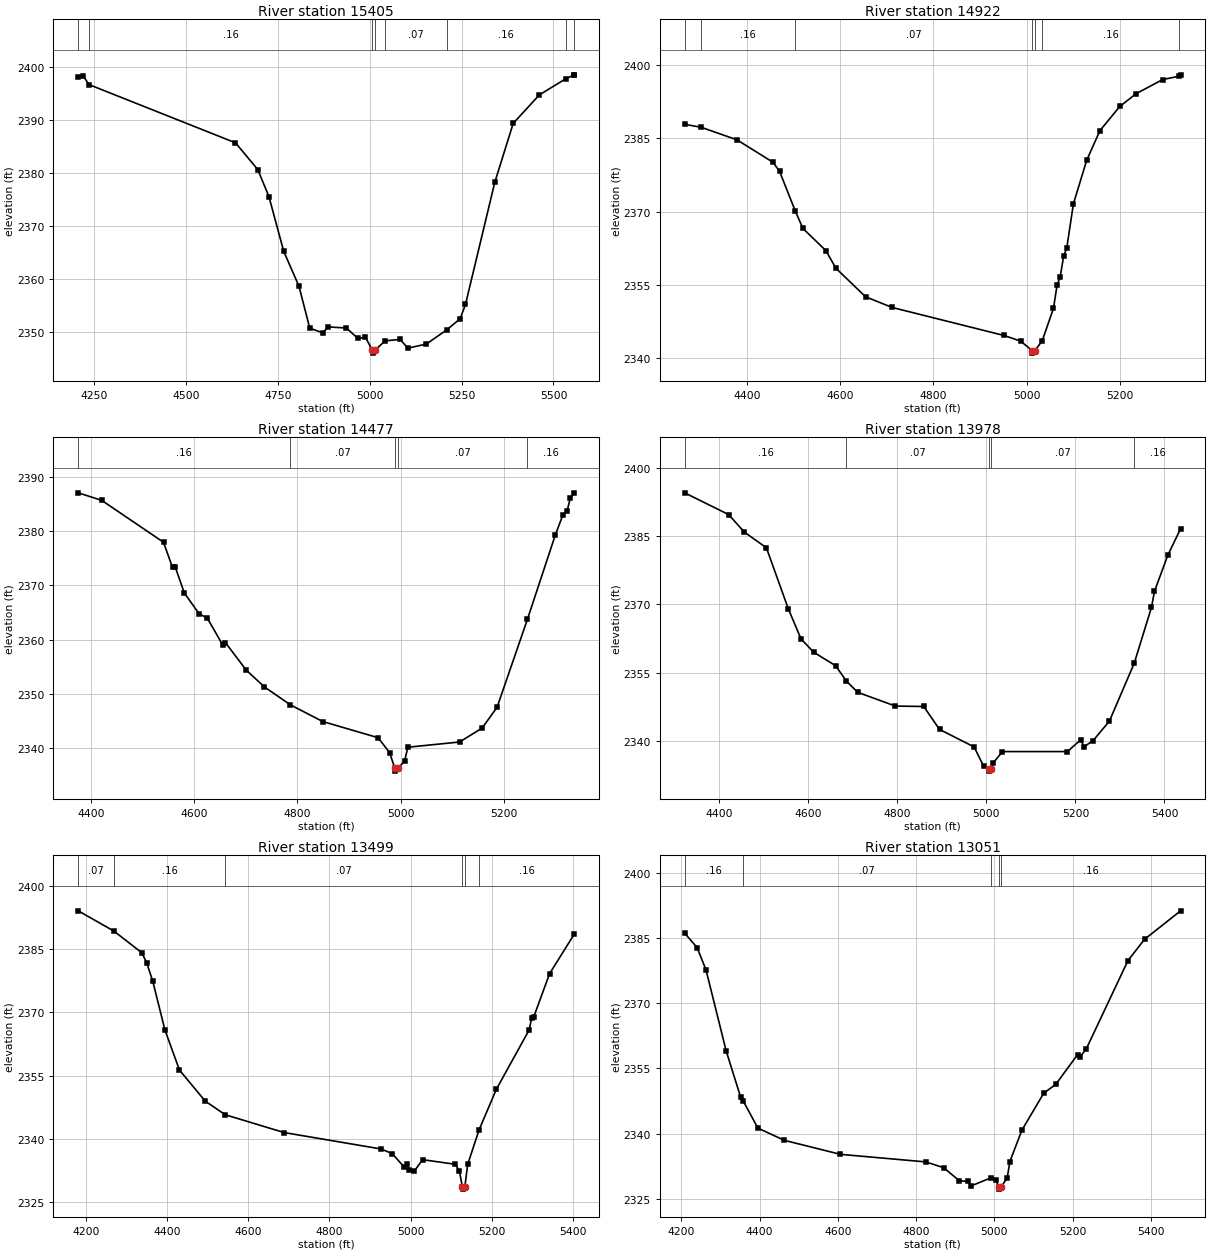
Type RM Length L Ch R = 1,15405,483,483,483
BEGIN DESCRIPTION:
elmc23
END DESCRIPTION:
XS GIS Cut Line= 3
      1483721.34      6777610.01      1484506.85      6777494.24
      1484957.16      6777167.61
#Sta/Elev= 30
  4206.0 2398.16  4219.8 2398.35  4235.2 2396.74  4634.2 2385.74  4694.9 2380.69
  4725.2 2375.59  4765.6 2365.24  4806.9 2358.68  4836.4 2350.74  4871.6 2349.86
  4886.9 2350.97  4936.2 2350.76  4967.8 2348.79  4988.0 2349.03  5007.2 2346.52
  5007.7 2346.02  5012.9 2346.52  5041.9 2348.34  5082.6 2348.61  5103.5 2346.96
  5153.8 2347.73  5209.6 2350.42  5245.8 2352.51  5260.4 2355.21  5340.1 2378.25
  5390.3 2389.41  5461.5 2394.79  5532.8 2397.81  5556.1 2398.58  5556.3 2398.58
#Mann=8,-1,0
  4206.0    0.07       0  4235.2    0.16       0  5007.2    0.07       0
  5012.9    0.16       0  5041.9    0.07       0  5209.6    0.16       0
  5532.8    0.07       0  5556.1    0.16       0
Bank Sta=5007.2,5012.9
Exp/Cntr=0.3,0.1

Type RM Length L Ch R = 1,14922,445,445,445
BEGIN DESCRIPTION:
elmc22
END DESCRIPTION:
XS GIS Cut Line= 3
      1484356.02      6778187.11      1484894.72      6777688.99
      1485143.30      6777471.79
#Sta/Elev= 30
  4266.3 2387.86  4301.6 2387.25  4378.1 2384.70  4455.8 2380.09  4469.9 2378.21
  4503.4 2370.15  4519.8 2366.56  4569.1 2362.01  4590.7 2358.40  4654.2 2352.56
  4710.9 2350.38  4951.3 2344.63  4986.8 2343.49  5011.8 2341.52  5012.3 2341.02
  5017.6 2341.52  5033.3 2343.57  5057.4 2350.20  5065.0 2354.88  5071.7 2356.61
  5079.3 2360.92  5085.9 2362.55  5100.1 2371.57  5128.6 2380.49  5157.1 2386.58
  5199.6 2391.51  5234.9 2394.15  5291.9 2397.03  5326.9 2397.71  5330.1 2397.99
#Mann=7,-1,0
  4266.3    0.07       0  4301.6    0.16       0  4503.4    0.07       0
  5011.8    0.07       0  5017.6    0.07       0  5033.3    0.16       0
  5326.9    0.07       0
Bank Sta=5011.8,5017.6
Exp/Cntr=0.3,0.1

Type RM Length L Ch R = 1,14477,499,499,499
BEGIN DESCRIPTION:
elmc21
END DESCRIPTION:
XS GIS Cut Line= 3
      1484437.83      6778321.72      1485004.54      6778058.16
      1485204.99      6777788.01
#Sta/Elev= 30
  4375.0 2387.05  4420.4 2385.67  4540.4 2377.93  4557.8 2373.28  4563.3 2373.32
  4580.6 2368.60  4609.0 2364.79  4625.5 2363.91  4654.8 2359.04  4660.3 2359.44
  4700.6 2354.37  4735.8 2351.27  4786.2 2347.96  4848.9 2344.88  4956.4 2341.89
  4978.5 2339.16  4988.9 2336.23  4989.3 2335.73  4994.7 2336.23  5007.8 2337.62
  5014.0 2340.14  5114.2 2341.10  5158.0 2343.67  5187.0 2347.51  5245.8 2363.72
  5299.9 2379.28  5314.5 2382.96  5322.9 2383.77  5329.1 2386.15  5336.4 2387.04
#Mann=5,-1,0
  4375.0    0.16       0  4786.2    0.07       0  4988.9    0.07       0
  4994.7    0.07       0  5245.8    0.16       0
Bank Sta=4988.9,4994.7
Exp/Cntr=0.3,0.1

Type RM Length L Ch R = 1,13978,479,479,479
BEGIN DESCRIPTION:
elmc20
END DESCRIPTION:
XS GIS Cut Line= 3
      1484846.58      6778889.15      1485324.80      6778408.67
      1485554.98      6778038.03
#Sta/Elev= 30
  4322.1 2394.55  4420.8 2389.77  4456.1 2385.92  4505.7 2382.46  4555.1 2368.99
  4583.4 2362.43  4611.7 2359.50  4661.2 2356.52  4685.5 2353.13  4710.7 2350.67
  4795.6 2347.64  4859.2 2347.55  4894.6 2342.51  4972.4 2338.65  4993.5 2334.46
  5005.3 2333.83  5005.8 2333.33  5011.3 2333.83  5014.2 2335.01  5036.1 2337.63
  5181.9 2337.63  5212.6 2340.28  5218.5 2338.64  5239.7 2340.04  5276.3 2344.33
  5332.1 2357.07  5370.8 2369.35  5377.5 2372.86  5407.4 2380.81  5436.3 2386.66
#Mann=5,-1,0
  4322.1    0.16       0  4685.5    0.07       0  5005.3    0.07       0
  5011.3    0.07       0  5332.1    0.16       0
Bank Sta=5005.3,5011.3
Exp/Cntr=0.3,0.1

Type RM Length L Ch R = 1,13499,448,448,448
BEGIN DESCRIPTION:
elmc19
END DESCRIPTION:
XS GIS Cut Line= 3
      1485288.95      6779168.10      1485746.73      6778487.66
      1485805.00      6778087.98
#Sta/Elev= 30
  4179.9 2394.10  4267.9 2389.30  4336.7 2384.17  4348.9 2381.78  4363.9 2377.42
  4393.8 2365.88  4429.8 2356.34  4493.4 2348.98  4542.7 2345.75  4687.8 2341.53
  4927.3 2337.63  4954.8 2336.54  4984.7 2333.31  4990.8 2334.13  4996.8 2332.64
  5009.8 2332.45  5030.0 2335.09  5110.8 2334.00  5120.9 2332.32  5128.0 2328.61
  5128.5 2328.11  5134.1 2328.61  5141.1 2333.95  5169.1 2342.13  5211.9 2351.79
  5292.7 2365.83  5298.8 2368.57  5303.9 2368.87  5343.2 2379.19  5403.9 2388.54
#Mann=6,-1,0
  4179.9    0.07       0  4267.9    0.16       0  4542.7    0.07       0
  5128.0    0.07       0  5134.1    0.07       0  5169.1    0.16       0
Bank Sta=5128,5134.1
Exp/Cntr=0.3,0.1

Type RM Length L Ch R = 1,13051,467,467,467
BEGIN DESCRIPTION:
elmc18
END DESCRIPTION:
XS GIS Cut Line= 3
      1485805.01      6779287.98      1486135.99      6778568.89
      1486298.23      6778121.39
#Sta/Elev= 30
  4208.4 2386.08  4240.1 2382.79  4263.0 2377.61  4314.5 2358.99  4351.5 2348.36
  4358.1 2347.50  4395.5 2341.25  4463.3 2338.44  4606.6 2335.22  4824.8 2333.48
  4870.2 2332.15  4910.7 2329.13  4933.6 2329.00  4939.1 2327.91  4991.5 2329.83
  5003.1 2329.39  5011.2 2327.72  5011.7 2327.22  5017.4 2327.72  5032.9 2329.88
  5039.6 2333.56  5070.3 2340.78  5126.2 2349.30  5156.8 2351.30  5212.8 2358.18
  5218.1 2357.52  5235.0 2359.50  5341.3 2379.77  5383.9 2384.69  5476.0 2391.23
#Mann=5,-1,0
  4208.4    0.16       0  4358.1    0.07       0  4991.5    0.16       0
  5011.2    0.07       0  5017.4    0.16       0
Bank Sta=5011.2,5017.4
Exp/Cntr=0.3,0.1

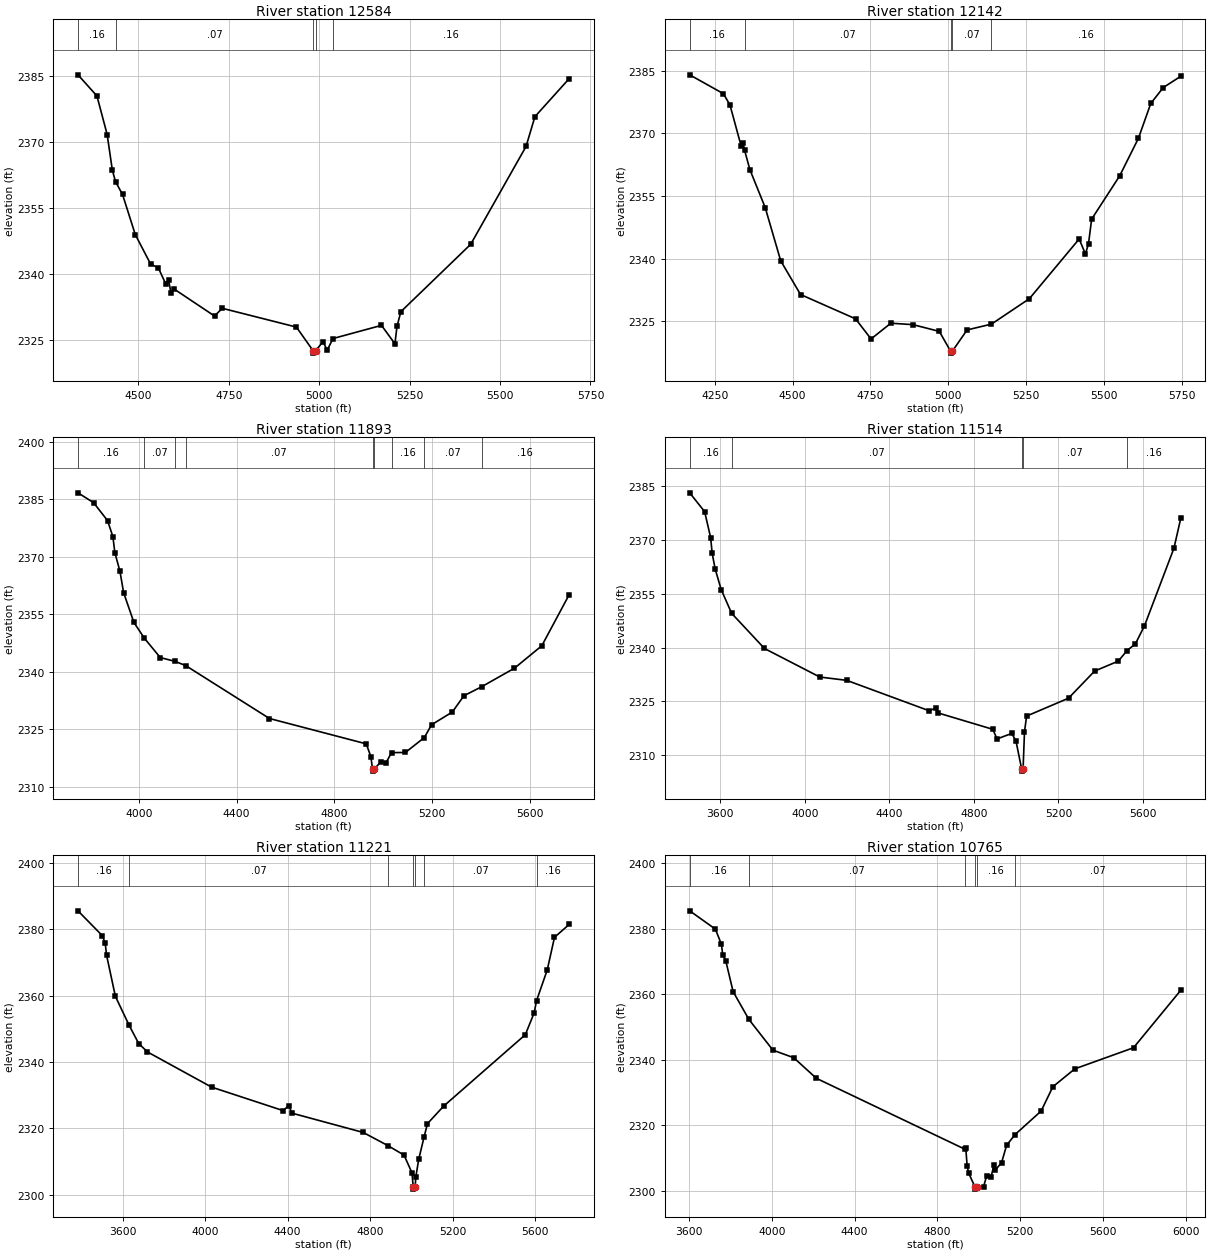
Type RM Length L Ch R = 1,12584,442,442,442
BEGIN DESCRIPTION:
elmc17
END DESCRIPTION:
XS GIS Cut Line= 3
      1485942.97      6779370.05      1486424.63      6778908.64
      1486673.89      6778264.06
#Sta/Elev= 30
  4333.0 2385.25  4385.4 2380.46  4413.7 2371.71  4427.9 2363.68  4436.8 2361.00
  4456.2 2358.11  4491.4 2349.01  4533.9 2342.31  4555.2 2341.44  4576.3 2337.72
  4583.5 2338.65  4590.5 2335.64  4597.7 2336.71  4710.6 2330.53  4732.0 2332.28
  4937.0 2328.02  4983.5 2322.61  4984.0 2322.11  4989.8 2322.61  5010.5 2324.71
  5022.1 2322.79  5038.2 2325.42  5172.2 2328.41  5209.4 2324.23  5215.1 2328.18
  5225.8 2331.51  5418.8 2346.79  5571.9 2368.99  5596.4 2375.75  5691.1 2384.38
#Mann=5,-1,0
  4333.0    0.16       0  4436.8    0.07       0  4983.5    0.07       0
  4989.8    0.07       0  5038.2    0.16       0
Bank Sta=4983.5,4989.8
Exp/Cntr=0.3,0.1

Type RM Length L Ch R = 1,12142,249,249,249
BEGIN DESCRIPTION:
elmc16
END DESCRIPTION:
XS GIS Cut Line= 3
      1486265.17      6779591.24      1486836.18      6778988.18
      1486837.40      6778241.48
#Sta/Elev= 30
  4169.5 2384.04  4277.8 2379.52  4298.8 2376.83  4334.4 2367.06  4341.3 2367.59
  4345.8 2365.95  4362.7 2361.34  4412.1 2352.20  4461.8 2339.46  4525.4 2331.39
  4702.1 2325.56  4751.9 2320.74  4815.4 2324.51  4886.2 2324.17  4971.1 2322.55
  5007.0 2317.84  5007.5 2317.34  5013.3 2317.84  5060.2 2322.90  5138.4 2324.29
  5260.2 2330.38  5420.2 2344.70  5440.2 2341.10  5450.2 2343.58  5460.2 2349.45
  5550.2 2359.82  5610.2 2368.79  5650.2 2377.19  5690.2 2380.99  5746.7 2383.71
#Mann=5,-1,0
  4169.5    0.16       0  4345.8    0.07       0  5007.0    0.07       0
  5013.3    0.07       0  5138.4    0.16       0
Bank Sta=5007,5013.3
Exp/Cntr=0.3,0.1

Type RM Length L Ch R = 1,11893,379,379,379
BEGIN DESCRIPTION:
elmc15
END DESCRIPTION:
XS GIS Cut Line= 4
      1486404.63      6780086.54      1487059.59      6779113.64
      1487094.31      6778840.20      1486991.29      6778288.08
#Sta/Elev= 30
  3751.0 2386.74  3814.9 2384.17  3871.9 2379.50  3893.9 2375.30  3901.9 2371.13
  3922.9 2366.21  3937.9 2360.65  3979.9 2352.90  4023.0 2348.75  4087.9 2343.72
  4146.8 2342.76  4191.3 2341.65  4534.7 2327.81  4930.8 2321.19  4949.7 2317.84
  4956.5 2314.57  4957.0 2314.07  4963.0 2314.57  4990.0 2316.48  5010.8 2316.14
  5034.2 2318.90  5090.9 2318.94  5168.6 2322.84  5198.0 2326.18  5283.1 2329.50
  5330.4 2333.75  5402.5 2336.09  5537.4 2340.95  5649.3 2346.81  5761.1 2360.13
#Mann=9,-1,0
  3751.0    0.16       0  4023.0    0.07       0  4146.8    0.16       0
  4191.3    0.07       0  4956.5    0.07       0  4963.0    0.07       0
  5034.2    0.16       0  5168.6    0.07       0  5402.5    0.16       0
Bank Sta=4956.5,4963
Exp/Cntr=0.3,0.1

Type RM Length L Ch R = 1,11514,293,293,293
BEGIN DESCRIPTION:
elma818
END DESCRIPTION:
XS GIS Cut Line= 4
      1486464.96      6780038.13      1487346.04      6779083.26
      1487346.04      6778762.08      1486995.34      6778151.59
#Sta/Elev= 30
  3455.0 2383.20  3525.7 2377.95  3554.1 2370.72  3561.4 2366.33  3575.6 2361.93
  3604.0 2356.21  3653.6 2349.57  3809.0 2339.76  4070.7 2331.80  4198.2 2330.87
  4587.2 2322.41  4623.0 2323.15  4629.8 2321.79  4889.5 2317.21  4909.5 2314.52
  4979.5 2316.07  4999.5 2313.86  5026.3 2306.04  5026.8 2305.54  5032.8 2306.04
  5039.5 2316.53  5049.5 2320.90  5247.8 2325.89  5371.4 2333.46  5483.6 2336.24
  5525.0 2339.20  5564.1 2341.03  5607.2 2346.07  5746.7 2367.73  5779.5 2376.20
#Mann=5,-1,0
  3455.0    0.16       0  3653.6    0.07       0  5026.3    0.07       0
  5032.8    0.07       0  5525.0    0.16       0
Bank Sta=5026.3,5032.8
Exp/Cntr=0.3,0.1

Type RM Length L Ch R = 1,11221,456,456,456
BEGIN DESCRIPTION:
elmc14
END DESCRIPTION:
XS GIS Cut Line= 3
      1486457.49      6780076.97      1487605.00      6778938.00
      1488109.61      6778362.63
#Sta/Elev= 30
  3383.2 2385.61  3500.9 2378.14  3515.1 2375.88  3522.1 2372.16  3564.5 2359.84
  3631.7 2351.03  3677.7 2345.59  3720.1 2343.05  4031.2 2332.44  4377.8 2325.36
  4406.0 2326.86  4420.2 2324.60  4766.6 2318.76  4885.9 2314.81  4964.6 2311.93
  5003.3 2306.55  5009.1 2302.17  5009.6 2301.67  5018.4 2302.17  5021.4 2305.22
  5035.6 2310.62  5061.8 2317.41  5078.3 2321.43  5156.1 2326.67  5552.8 2348.25
  5595.5 2354.81  5607.3 2358.53  5659.1 2367.79  5694.2 2377.62  5765.3 2381.50
#Mann=7,-1,0
  3383.2    0.16       0  3631.7    0.07       0  4885.9    0.16       0
  5009.1    0.07       0  5018.4    0.16       0  5061.8    0.07       0
  5607.3    0.16       0
Bank Sta=5009.1,5018.4
Exp/Cntr=0.3,0.1

Type RM Length L Ch R = 1,10765,481,481,481
BEGIN DESCRIPTION:
elmc13
END DESCRIPTION:
XS GIS Cut Line= 4
      1486529.66      6780105.78      1487660.71      6779285.65
      1487773.67      6779209.20      1488332.23      6778582.21
#Sta/Elev= 30
  3602.9 2385.41  3726.9 2379.84  3756.3 2375.20  3762.4 2372.06  3777.1 2370.21
  3812.7 2360.78  3888.8 2352.31  4005.2 2342.92  4105.7 2340.62  4214.7 2334.35
  4933.4 2312.70  4936.9 2312.97  4943.5 2307.62  4951.6 2305.32  4982.5 2301.05
  4983.0 2300.55  4991.8 2301.05  5022.9 2301.34  5037.9 2304.60  5058.9 2304.33
  5073.8 2307.95  5079.9 2306.39  5109.8 2308.62  5134.2 2313.92  5174.9 2317.18
  5300.8 2324.35  5357.7 2331.77  5463.9 2337.23  5747.3 2343.66  5976.1 2361.22
#Mann=6,-1,0
  3602.9    0.16       0  3888.8    0.07       0  4933.4    0.16       0
  4982.5    0.07       0  4991.8    0.16       0  5174.9    0.07       0
Bank Sta=4982.5,4991.8
Exp/Cntr=0.3,0.1

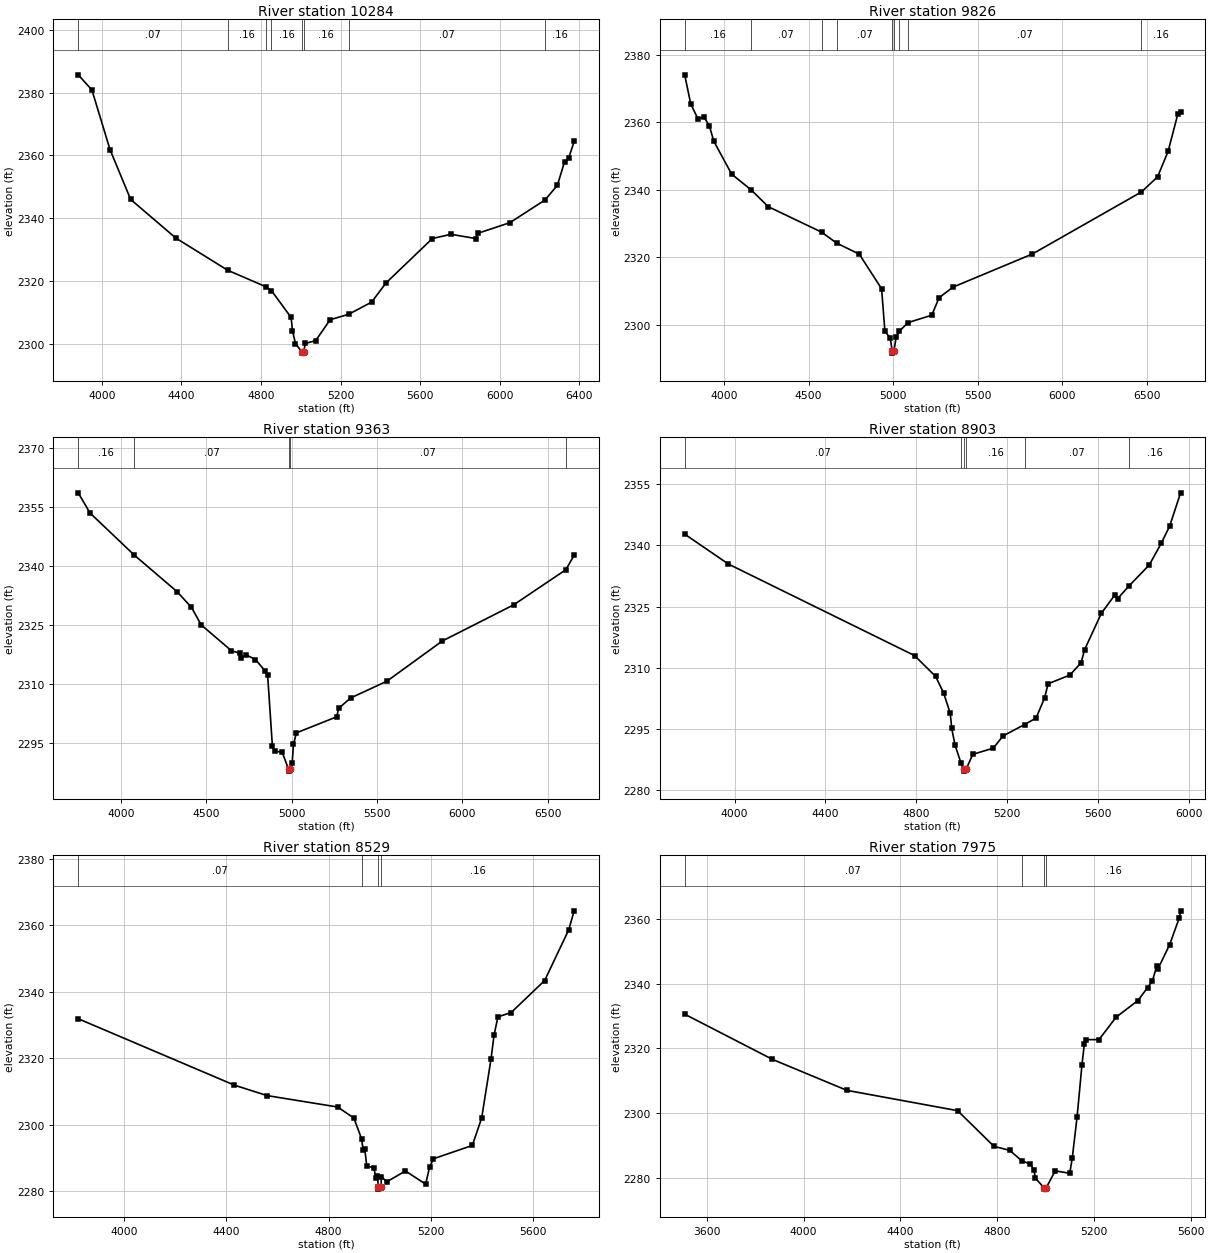
Type RM Length L Ch R = 1,10284,458,458,458
BEGIN DESCRIPTION:
elmc12
END DESCRIPTION:
XS GIS Cut Line= 3
      1486736.40      6780211.60      1487748.88      6779735.82
      1488495.94      6778582.18
#Sta/Elev= 30
  3881.3 2385.69  3950.1 2380.88  4041.3 2361.84  4144.9 2345.98  4371.6 2333.69
  4632.7 2323.41  4826.4 2318.11  4852.8 2316.91  4951.5 2308.37  4958.3 2304.21
  4973.6 2300.01  5004.6 2297.50  5005.1 2297.00  5014.0 2297.50  5023.8 2300.09
  5075.2 2301.00  5147.8 2307.64  5241.5 2309.40  5356.2 2313.25  5428.7 2319.37
  5661.5 2333.52  5755.1 2334.87  5879.0 2333.53  5891.0 2335.20  6051.2 2338.57
  6227.6 2345.79  6290.0 2350.47  6326.2 2358.00  6347.3 2359.23  6374.4 2364.46
#Mann=8,-1,0
  3881.3    0.07       0  4632.7    0.16       0  4826.4    0.07       0
  4852.8    0.16       0  5004.6    0.07       0  5014.0    0.16       0
  5241.5    0.07       0  6227.6    0.16       0
Bank Sta=5004.6,5014
Exp/Cntr=0.3,0.1

Type RM Length L Ch R = 1,9826,463,463,463
BEGIN DESCRIPTION:
elmc11
END DESCRIPTION:
XS GIS Cut Line= 4
      1486741.21      6780528.98      1487911.10      6780140.19
      1488049.61      6779995.76      1488534.93      6778576.56
#Sta/Elev= 30
  3767.2 2374.11  3802.8 2365.53  3844.6 2361.15  3881.6 2361.57  3913.2 2358.98
  3939.6 2354.40  4045.2 2344.65  4159.1 2340.06  4261.5 2335.02  4576.8 2327.47
  4665.5 2324.23  4799.7 2320.94  4931.6 2310.69  4951.4 2298.03  4983.0 2296.10
  4994.7 2292.10  4995.2 2291.60  5004.1 2292.10  5018.3 2296.42  5037.4 2298.13
  5087.8 2300.65  5228.2 2302.84  5271.7 2308.03  5353.4 2311.16  5823.0 2320.98
  6468.5 2339.39  6563.8 2343.86  6626.4 2351.50  6683.7 2362.53  6700.0 2362.95
#Mann=9,-1,0
  3767.2    0.16       0  4159.1    0.07       0  4576.8    0.16       0
  4665.5    0.07       0  4994.7    0.07       0  5004.1    0.07       0
  5037.4    0.16       0  5087.8    0.07       0  6468.5    0.16       0
Bank Sta=4994.7,5004.1
Exp/Cntr=0.3,0.1

Type RM Length L Ch R = 1,9363,460,460,460
BEGIN DESCRIPTION:
elmc10
END DESCRIPTION:
XS GIS Cut Line= 3
      1487414.46      6781245.50      1488275.15      6780337.64
      1488549.35      6778706.42
#Sta/Elev= 30
  3749.0 2358.63  3818.3 2353.49  4076.6 2342.82  4327.6 2333.50  4412.5 2329.49
  4469.1 2325.04  4645.9 2318.48  4695.6 2317.79  4702.5 2316.51  4730.8 2317.45
  4787.5 2316.21  4844.1 2313.29  4858.3 2312.39  4886.6 2294.10  4900.7 2292.82
  4943.2 2292.71  4980.9 2288.32  4981.4 2287.82  4990.5 2288.32  5002.4 2289.86
  5009.8 2294.60  5027.1 2297.56  5263.3 2301.64  5274.5 2303.79  5344.4 2306.42
  5557.4 2310.71  5881.8 2320.93  6299.4 2330.12  6605.0 2339.05  6654.1 2342.75
#Mann=5,-1,0
  3749.0    0.16       0  4076.6    0.07       0  4980.9    0.07       0
  4990.5    0.07       0  6605.0    0.16       0
Bank Sta=4980.9,4990.5
Exp/Cntr=0.3,0.1

Type RM Length L Ch R = 1,8903,374,374,374
BEGIN DESCRIPTION:
elmc9
END DESCRIPTION:
XS GIS Cut Line= 3
      1487895.34      6781538.83      1488648.92      6780579.91
      1489130.62      6779746.15
#Sta/Elev= 30
  3780.4 2342.78  3972.3 2335.45  4792.0 2313.00  4885.0 2307.87  4920.3 2303.78
  4949.2 2298.80  4955.5 2295.18  4970.0 2291.08  4995.7 2286.76  5008.5 2285.17
  5009.0 2284.67  5019.1 2285.17  5048.4 2288.79  5138.5 2290.30  5181.6 2293.31
  5276.3 2296.10  5326.7 2297.68  5364.0 2302.57  5379.7 2306.08  5475.7 2308.23
  5524.8 2311.25  5540.6 2314.48  5614.3 2323.39  5672.0 2327.75  5685.6 2326.96
  5736.9 2330.14  5824.8 2335.21  5877.9 2340.54  5914.6 2344.74  5962.9 2352.90
#Mann=6,-1,0
  3780.4    0.07       0  4995.7    0.16       0  5008.5    0.07       0
  5019.1    0.16       0  5276.3    0.07       0  5736.9    0.16       0
Bank Sta=5008.5,5019.1
Exp/Cntr=0.3,0.1

Type RM Length L Ch R = 1,8529,554,554,554
BEGIN DESCRIPTION:
elmc8
END DESCRIPTION:
XS GIS Cut Line= 3
      1488227.13      6781524.43      1488991.79      6780661.44
      1489409.23      6779991.82
#Sta/Elev= 30
  3819.5 2331.89  4431.5 2311.88  4559.5 2308.74  4835.5 2305.31  4899.0 2301.98
  4929.1 2295.77  4935.0 2292.46  4941.7 2292.71  4949.2 2287.65  4977.5 2286.91
  4985.3 2283.96  4991.1 2284.62  4994.8 2281.08  4995.3 2280.58  5005.4 2281.08
  5006.5 2284.37  5027.7 2282.78  5100.9 2286.05  5179.9 2282.08  5195.3 2287.14
  5210.6 2289.73  5362.8 2293.73  5399.4 2301.97  5436.0 2319.75  5447.9 2326.94
  5463.1 2332.46  5515.0 2333.77  5646.0 2343.39  5740.4 2358.67  5761.6 2364.39
#Mann=4,-1,0
  3819.5    0.07       0  4929.1    0.16       0  4994.8    0.07       0
  5005.4    0.16       0
Bank Sta=4994.8,5005.4
Exp/Cntr=0.3,0.1

Type RM Length L Ch R = 1,7975,419,419,419
BEGIN DESCRIPTION:
elmc7
END DESCRIPTION:
XS GIS Cut Line= 3
      1488280.02      6781519.61      1489482.51      6780637.90
      1489539.90      6780082.35
#Sta/Elev= 30
  3508.9 2330.53  3871.8 2316.54  4179.1 2306.97  4636.8 2300.68  4787.3 2289.64
  4852.1 2288.41  4901.5 2285.20  4937.8 2284.15  4952.4 2282.22  4958.6 2279.77
  4993.1 2276.91  4993.6 2276.41  5003.7 2276.91  5040.1 2282.06  5100.4 2281.31
  5110.5 2285.94  5130.6 2298.72  5150.7 2314.82  5160.7 2321.31  5168.0 2322.66
  5221.1 2322.65  5291.4 2329.56  5381.9 2334.75  5422.1 2338.74  5442.2 2340.91
  5459.7 2345.36  5464.8 2344.52  5512.6 2351.95  5552.8 2360.26  5558.5 2362.50
#Mann=4,-1,0
  3508.9    0.07       0  4901.5    0.16       0  4993.1    0.07       0
  5003.7    0.16       0
Bank Sta=4993.1,5003.7
Exp/Cntr=0.3,0.1