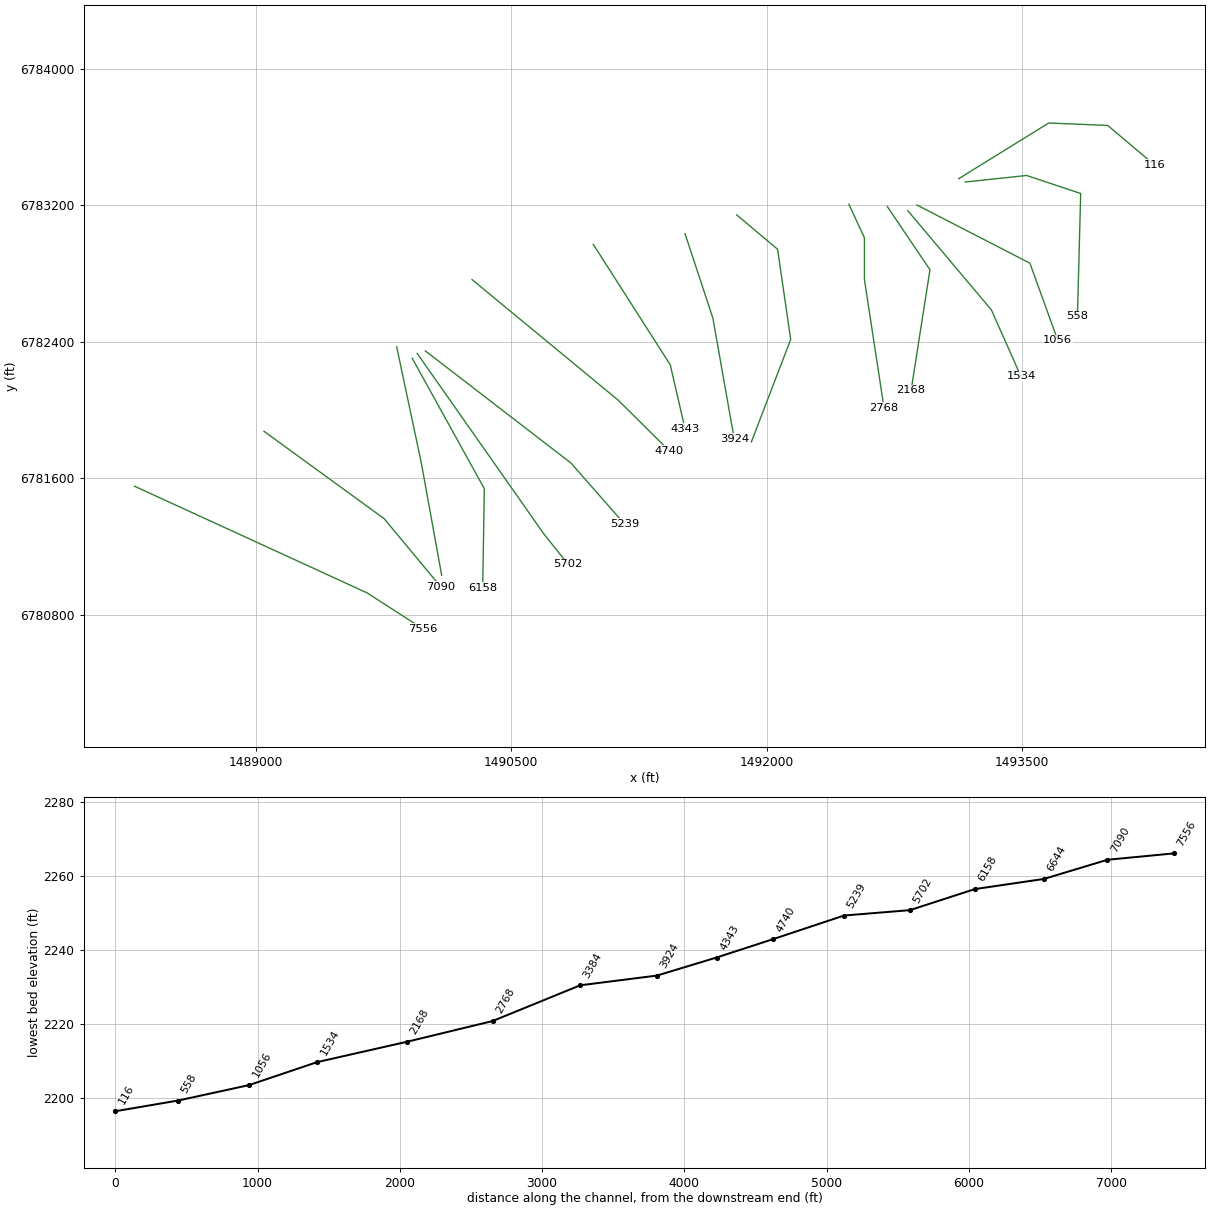
HEC-RAS study Elm 18.prj: Elm 18 Base Level Engineering

--- Elm 18.g01 (geometry) --- (continued)

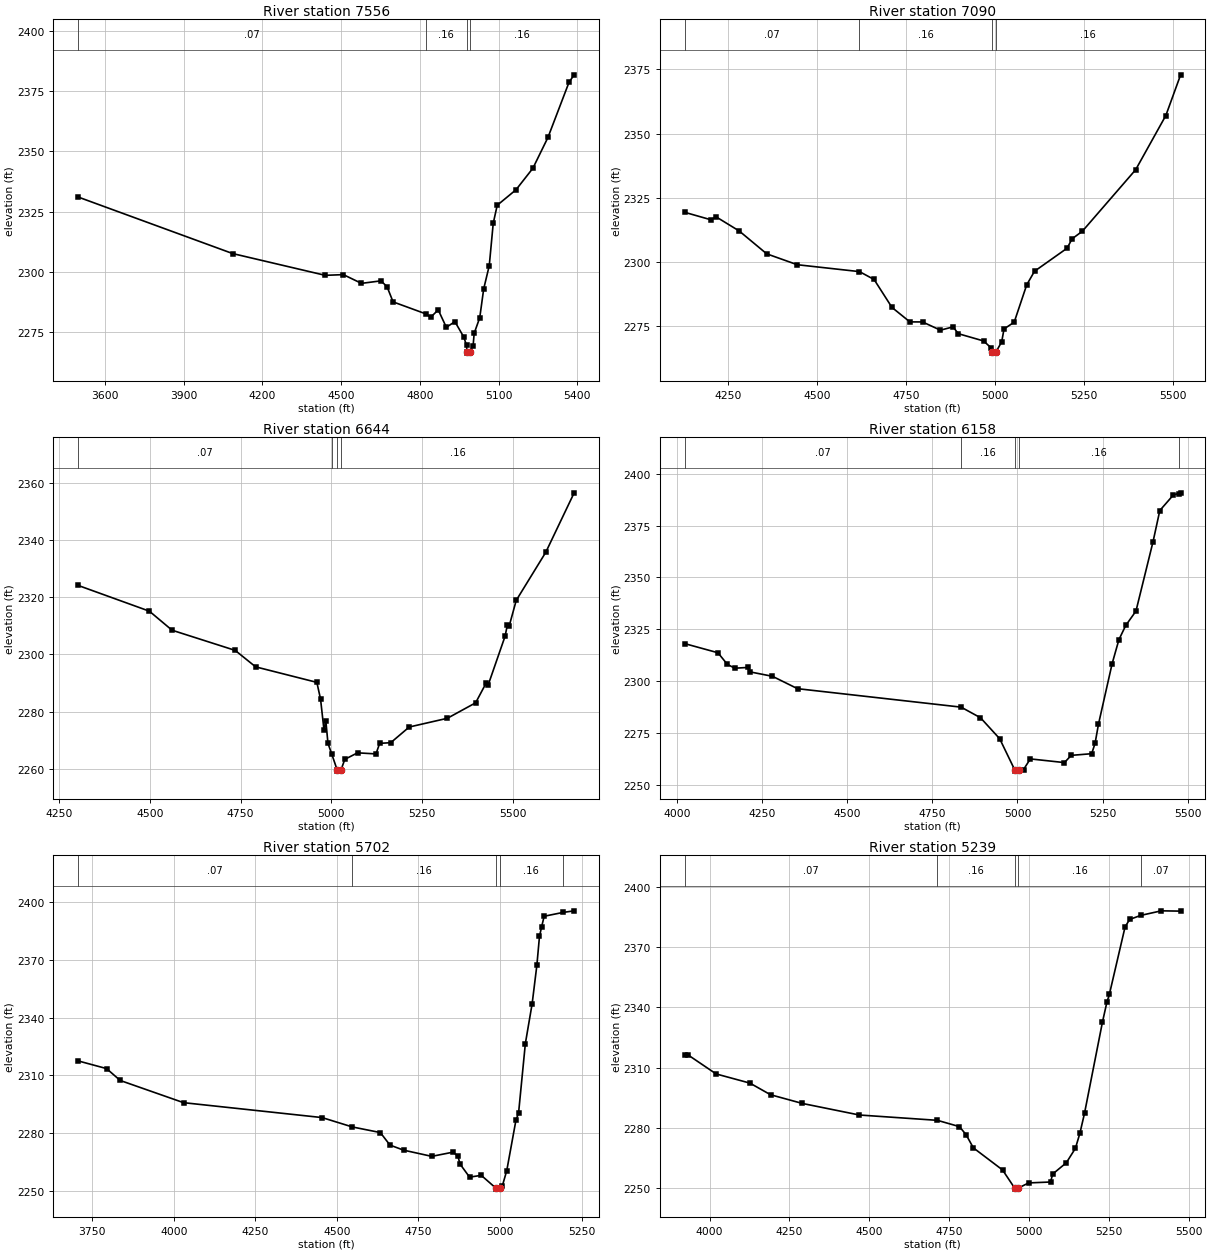
Type RM Length L Ch R = 1,7556,466,466,466
BEGIN DESCRIPTION:
elmc6
END DESCRIPTION:
XS GIS Cut Line= 3
      1488289.71      6781553.23      1489655.00      6780927.39
      1489981.19      6780717.28
#Sta/Elev= 30
  3498.1 2331.01  4086.9 2307.51  4439.5 2298.47  4508.5 2298.76  4577.5 2295.13
  4652.0 2296.18  4675.0 2293.73  4698.0 2287.43  4822.2 2282.47  4841.5 2281.07
  4870.0 2284.11  4901.0 2276.85  4933.5 2279.23  4967.5 2272.80  4978.0 2269.33
  4979.6 2266.63  4980.1 2266.13  4990.4 2266.63  5003.0 2269.27  5007.0 2274.37
  5028.2 2280.84  5043.3 2292.84  5064.5 2302.50  5079.6 2320.08  5094.8 2327.60
  5166.5 2334.05  5230.8 2342.99  5288.3 2355.83  5368.7 2378.79  5388.0 2381.82
#Mann=4,-1,0
  3498.1    0.07       0  4822.2    0.16       0  4979.6    0.07       0
  4990.4    0.16       0
Bank Sta=4979.6,4990.4
Exp/Cntr=0.3,0.1

Type RM Length L Ch R = 1,7090,446,446,446
BEGIN DESCRIPTION:
elmc5
END DESCRIPTION:
XS GIS Cut Line= 3
      1489049.44      6781875.46      1489754.94      6781362.80
      1490087.65      6780962.39
#Sta/Elev= 30
  4127.9 2319.32  4201.4 2316.41  4216.1 2317.55  4281.1 2312.03  4358.3 2303.12
  4444.1 2298.88  4618.8 2296.19  4659.8 2293.12  4710.0 2282.23  4760.3 2276.59
  4795.8 2276.57  4846.1 2273.36  4881.6 2274.65  4896.3 2271.99  4967.4 2269.15
  4988.3 2266.47  4991.3 2264.91  4991.8 2264.41  5002.2 2264.91  5018.1 2268.79
  5024.7 2273.83  5053.3 2276.49  5088.4 2291.03  5110.3 2296.33  5201.7 2305.31
  5216.0 2309.00  5244.7 2311.94  5394.4 2335.93  5479.1 2357.06  5520.6 2372.92
#Mann=4,-1,0
  4127.9    0.07       0  4618.8    0.16       0  4991.3    0.07       0
  5002.2    0.16       0
Bank Sta=4991.3,5002.2
Exp/Cntr=0.3,0.1

Type RM Length L Ch R = 1,6644,486,486,486
BEGIN DESCRIPTION:
elmc4
END DESCRIPTION:
XS GIS Cut Line= 3
      1489828.49      6782370.75      1489973.33      6781688.75
      1490092.61      6781031.09
#Sta/Elev= 30
  4302.8 2324.06  4498.7 2315.08  4561.2 2308.43  4735.0 2301.39  4791.3 2295.64
  4959.9 2290.22  4970.1 2284.38  4979.6 2273.54  4984.7 2276.73  4990.5 2268.94
  5000.5 2265.35  5015.6 2259.73  5016.1 2259.23  5026.6 2259.73  5036.9 2263.34
  5071.9 2265.62  5122.7 2265.24  5132.9 2268.93  5163.4 2269.16  5214.2 2274.63
  5319.2 2277.68  5397.1 2283.08  5426.1 2290.00  5431.2 2289.14  5478.4 2306.41
  5484.6 2310.40  5489.7 2309.98  5508.9 2318.85  5590.2 2335.63  5668.4 2356.40
#Mann=4,-1,0
  4302.8    0.07       0  5000.5    0.16       0  5015.6    0.07       0
  5026.6    0.16       0
Bank Sta=5015.6,5026.6
Exp/Cntr=0.3,0.1

Type RM Length L Ch R = 1,6158,456,456,456
BEGIN DESCRIPTION:
elmc3
END DESCRIPTION:
XS GIS Cut Line= 3
      1489919.86      6782303.43      1490343.03      6781538.83
      1490333.42      6780956.91
#Sta/Elev= 30
  4023.1 2318.03  4120.7 2313.62  4148.3 2308.04  4170.1 2306.16  4207.9 2306.52
  4213.6 2304.43  4280.8 2302.25  4354.4 2296.28  4834.6 2287.37  4891.5 2282.25
  4947.8 2272.14  4992.3 2256.99  4992.8 2256.49  5003.3 2256.99  5017.8 2257.24
  5037.8 2262.39  5137.9 2260.61  5157.9 2264.10  5217.9 2264.90  5227.9 2269.94
  5237.9 2279.18  5277.9 2308.33  5297.9 2319.96  5317.9 2326.79  5347.9 2333.73
  5397.9 2367.13  5417.9 2382.26  5457.9 2389.80  5472.9 2390.46  5479.0 2390.80
#Mann=5,-1,0
  4023.1    0.07       0  4834.6    0.16       0  4992.3    0.07       0
  5003.3    0.16       0  5472.9    0.07       0
Bank Sta=4992.3,5003.3
Exp/Cntr=0.3,0.1

Type RM Length L Ch R = 1,5702,463,463,463
BEGIN DESCRIPTION:
elmc2
END DESCRIPTION:
XS GIS Cut Line= 3
      1489948.71      6782332.28      1490691.80      6781274.25
      1490833.53      6781096.42
#Sta/Elev= 30
  3707.1 2317.47  3794.0 2313.48  3835.9 2307.30  4030.0 2295.76  4454.6 2288.01
  4547.5 2283.13  4633.2 2280.22  4662.8 2273.70  4704.7 2271.06  4790.9 2267.84
  4856.3 2270.03  4871.1 2268.02  4877.2 2263.93  4906.8 2257.03  4942.6 2257.97
  4987.6 2251.30  4988.1 2250.80  4998.6 2251.30  5007.4 2252.55  5020.8 2260.44
  5049.0 2286.67  5057.0 2290.36  5077.8 2326.49  5098.6 2347.17  5113.1 2367.21
  5121.1 2382.21  5127.5 2387.09  5135.5 2392.70  5192.8 2394.67  5227.4 2395.52
#Mann=5,-1,0
  3707.1    0.07       0  4547.5    0.16       0  4987.6    0.07       0
  4998.6    0.16       0  5192.8    0.07       0
Bank Sta=4987.6,4998.6
Exp/Cntr=0.3,0.1

Type RM Length L Ch R = 1,5239,499,499,499
BEGIN DESCRIPTION:
elmc1
END DESCRIPTION:
XS GIS Cut Line= 3
      1489996.76      6782346.74      1490851.17      6781689.58
      1491164.91      6781332.54
#Sta/Elev= 30
  3922.1 2316.19  3933.5 2316.21  4020.6 2306.82  4126.5 2302.24  4190.9 2296.45
  4290.6 2292.10  4469.1 2286.33  4713.7 2283.67  4782.6 2280.53  4803.4 2276.52
  4826.1 2269.95  4917.6 2258.92  4955.6 2249.85  4956.1 2249.35  4966.6 2249.85
  4999.3 2252.45  5068.0 2252.90  5074.6 2256.87  5117.3 2262.50  5145.8 2269.71
  5160.0 2277.31  5174.3 2287.19  5230.3 2332.54  5244.5 2342.69  5252.1 2346.48
  5301.4 2380.21  5315.7 2383.90  5350.1 2385.91  5414.8 2388.20  5475.3 2388.05
#Mann=5,-1,0
  3922.1    0.07       0  4713.7    0.16       0  4955.6    0.07       0
  4966.6    0.16       0  5350.1    0.07       0
Bank Sta=4955.6,4966.6
Exp/Cntr=0.3,0.1

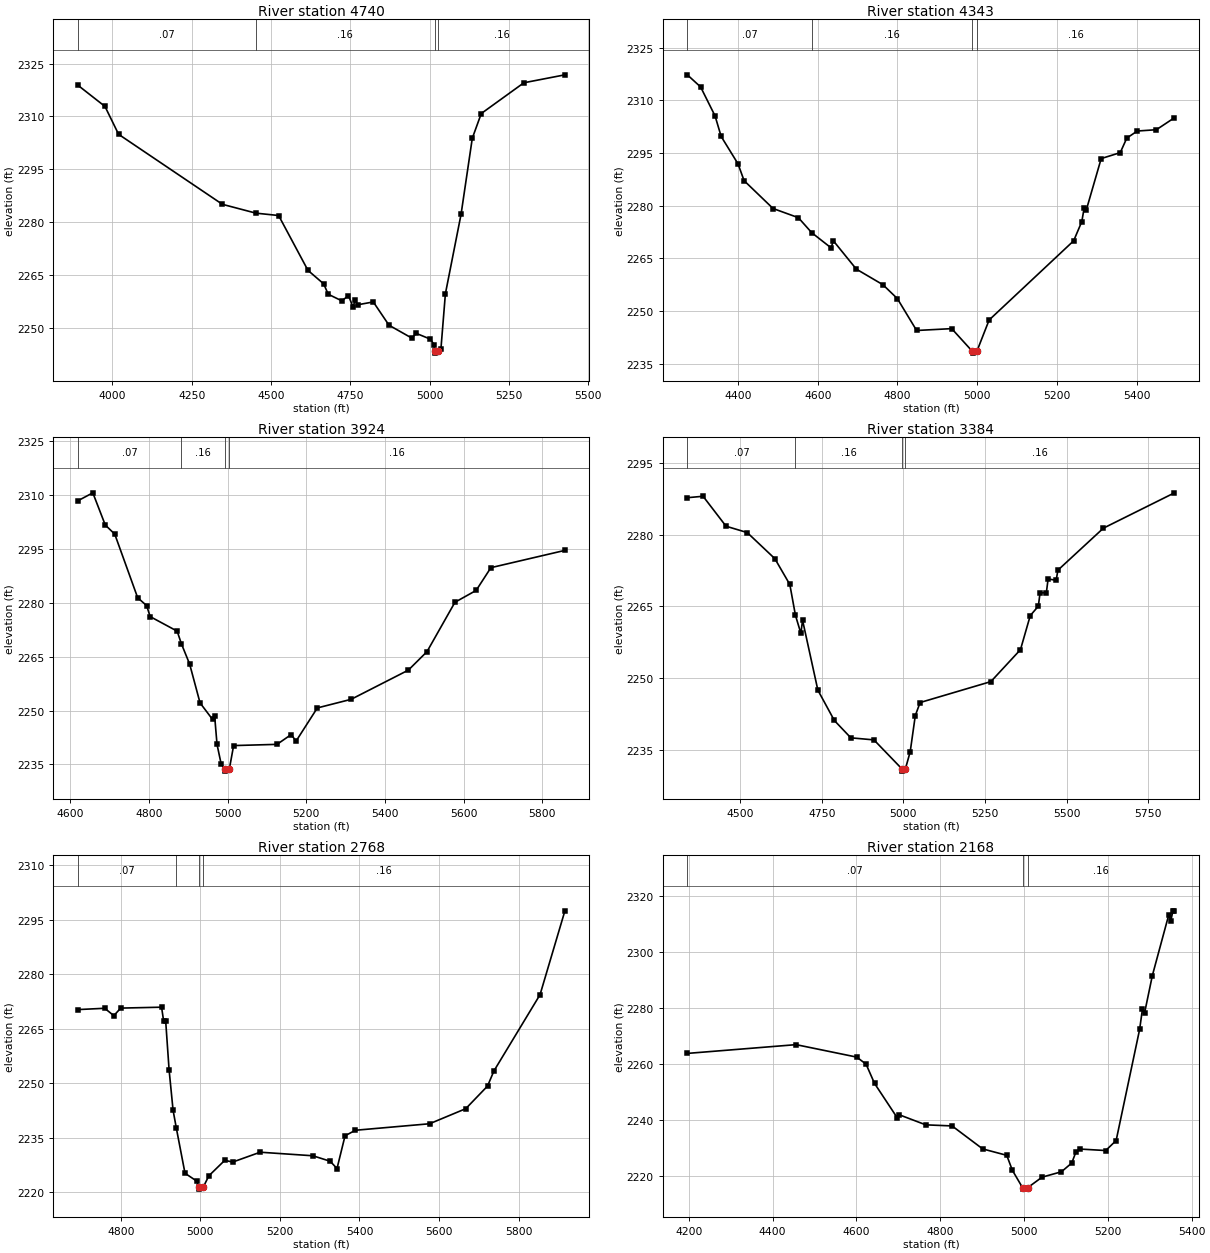
Type RM Length L Ch R = 1,4740,397,397,397
BEGIN DESCRIPTION:
elmc0
END DESCRIPTION:
XS GIS Cut Line= 3
      1490270.89      6782765.08      1491126.71      6782059.77
      1491429.83      6781760.03
#Sta/Elev= 30
  3891.0 2318.88  3976.7 2312.85  4019.7 2304.95  4346.8 2285.12  4452.4 2282.62
  4524.0 2281.95  4616.5 2266.41  4666.0 2262.59  4680.4 2259.65  4723.4 2257.77
  4744.2 2259.28  4758.6 2255.99  4765.0 2258.03  4772.9 2256.66  4822.4 2257.47
  4871.9 2250.88  4943.6 2247.24  4958.0 2248.56  5002.3 2246.93  5014.2 2245.33
  5015.7 2243.47  5016.2 2242.97  5026.8 2243.47  5035.4 2244.00  5049.6 2259.77
  5099.0 2282.29  5134.4 2303.83  5162.7 2310.84  5297.0 2319.55  5426.3 2321.80
#Mann=4,-1,0
  3891.0    0.07       0  4452.4    0.16       0  5015.7    0.07       0
  5026.8    0.16       0
Bank Sta=5015.7,5026.8
Exp/Cntr=0.3,0.1

Type RM Length L Ch R = 1,4343,419,419,419
BEGIN DESCRIPTION:
elmc288
END DESCRIPTION:
XS GIS Cut Line= 3
      1490982.60      6782971.87      1491434.64      6782264.96
      1491520.83      6781891.45
#Sta/Elev= 30
  4272.7 2317.30  4306.0 2313.85  4342.3 2305.58  4357.6 2299.74  4399.9 2291.93
  4415.1 2287.15  4487.8 2279.21  4551.3 2276.60  4584.9 2272.32  4633.3 2268.01
  4639.2 2270.00  4696.7 2261.95  4763.5 2257.50  4799.6 2253.56  4848.1 2244.46
  4936.1 2244.99  4988.0 2238.51  4988.5 2238.01  4999.2 2238.51  5030.0 2247.45
  5242.1 2270.01  5262.6 2275.50  5268.4 2279.32  5273.5 2278.66  5311.2 2293.44
  5359.0 2295.13  5375.5 2299.28  5401.8 2301.29  5449.7 2301.66  5495.1 2305.08
#Mann=4,-1,0
  4272.7    0.07       0  4584.9    0.16       0  4988.0    0.07       0
  4999.2    0.16       0
Bank Sta=4988,4999.2
Exp/Cntr=0.3,0.1

Type RM Length L Ch R = 1,3924,540,540,540
BEGIN DESCRIPTION:
elmc287
END DESCRIPTION:
XS GIS Cut Line= 3
      1491521.19      6783034.39      1491684.69      6782539.06
      1491809.66      6781832.54
#Sta/Elev= 30
  4618.7 2308.46  4657.0 2310.69  4688.6 2301.73  4712.8 2299.17  4771.0 2281.47
  4793.9 2279.25  4802.8 2276.20  4871.5 2272.14  4882.1 2268.67  4903.3 2262.95
  4929.7 2252.15  4961.5 2247.54  4966.8 2248.55  4972.9 2240.58  4983.5 2235.09
  4992.9 2233.63  4993.4 2233.13  5004.1 2233.63  5015.1 2240.25  5125.5 2240.59
  5161.7 2243.33  5173.9 2241.48  5228.0 2250.74  5314.0 2253.14  5459.6 2261.28
  5507.0 2266.43  5578.1 2280.19  5632.0 2283.49  5669.5 2289.83  5857.8 2294.65
#Mann=4,-1,0
  4618.7    0.07       0  4882.1    0.16       0  4992.9    0.07       0
  5004.1    0.16       0
Bank Sta=4992.9,5004.1
Exp/Cntr=0.3,0.1

Type RM Length L Ch R = 1,3384,616,616,616
BEGIN DESCRIPTION:
elmc286
END DESCRIPTION:
XS GIS Cut Line= 4
      1491824.18      6783144.94      1492064.59      6782943.00
      1492141.53      6782414.03      1491910.71      6781812.93
#Sta/Elev= 30
  4338.2 2287.74  4386.4 2288.04  4456.8 2281.77  4521.7 2280.44  4606.3 2274.98
  4652.2 2269.57  4669.4 2263.12  4686.1 2259.33  4691.2 2262.09  4738.1 2247.45
  4788.6 2241.10  4839.1 2237.47  4909.9 2237.04  4995.2 2231.00  4995.7 2230.50
  5006.4 2231.00  5021.0 2234.57  5036.6 2242.13  5051.3 2244.86  5268.1 2249.24
  5358.8 2255.93  5388.8 2263.06  5413.5 2265.03  5418.8 2267.81  5438.1 2267.87
  5443.5 2270.74  5468.1 2270.44  5473.5 2272.57  5612.8 2281.36  5830.6 2288.76
#Mann=4,-1,0
  4338.2    0.07       0  4669.4    0.16       0  4995.2    0.07       0
  5006.4    0.16       0
Bank Sta=4995.2,5006.4
Exp/Cntr=0.3,0.1

Type RM Length L Ch R = 1,2768,600,600,600
BEGIN DESCRIPTION:
elmc285
END DESCRIPTION:
XS GIS Cut Line= 4
      1492482.96      6783207.49      1492574.33      6783010.32
      1492574.33      6782765.07      1492689.51      6782011.58
#Sta/Elev= 30
  4691.7 2270.25  4759.4 2270.61  4782.3 2268.58  4799.7 2270.66  4902.4 2270.91
  4907.5 2267.16  4912.7 2267.16  4921.3 2253.67  4931.3 2242.55  4939.6 2237.58
  4961.3 2225.21  4991.3 2223.01  4995.7 2221.34  4996.2 2220.84  5007.0 2221.34
  5021.3 2224.51  5061.3 2228.77  5081.3 2228.29  5150.3 2231.00  5282.8 2230.02
  5326.2 2228.52  5343.5 2226.51  5363.7 2235.52  5389.7 2237.04  5576.2 2238.83
  5667.2 2242.98  5722.0 2249.21  5738.0 2253.36  5854.0 2274.36  5916.5 2297.43
#Mann=4,-1,0
  4691.7    0.07       0  4939.6    0.16       0  4995.7    0.07       0
  5007.0    0.16       0
Bank Sta=4995.7,5007
Exp/Cntr=0.3,0.1

Type RM Length L Ch R = 1,2168,634,634,634
BEGIN DESCRIPTION:
elmc284
END DESCRIPTION:
XS GIS Cut Line= 3
      1492708.99      6783193.03      1492959.03      6782822.78
      1492848.42      6782115.85
#Sta/Elev= 30
  4196.7 2263.80  4456.2 2266.93  4601.0 2262.47  4623.2 2259.94  4643.3 2253.08
  4697.9 2240.69  4702.9 2241.82  4765.6 2238.25  4828.4 2237.86  4901.4 2229.64
  4958.8 2227.35  4972.2 2222.00  4996.6 2215.76  4997.1 2215.26  5008.6 2215.76
  5043.1 2219.54  5089.3 2221.47  5113.9 2224.59  5124.0 2228.60  5134.2 2229.59
  5194.9 2229.06  5219.8 2232.64  5275.9 2272.41  5282.5 2279.55  5287.6 2278.23
  5306.2 2291.62  5345.2 2313.25  5350.3 2311.29  5355.4 2314.79  5359.0 2314.79
#Mann=3,-1,0
  4196.7    0.07       0  4996.6    0.07       0  5008.6    0.16       0
Bank Sta=4996.6,5008.6
Exp/Cntr=0.3,0.1

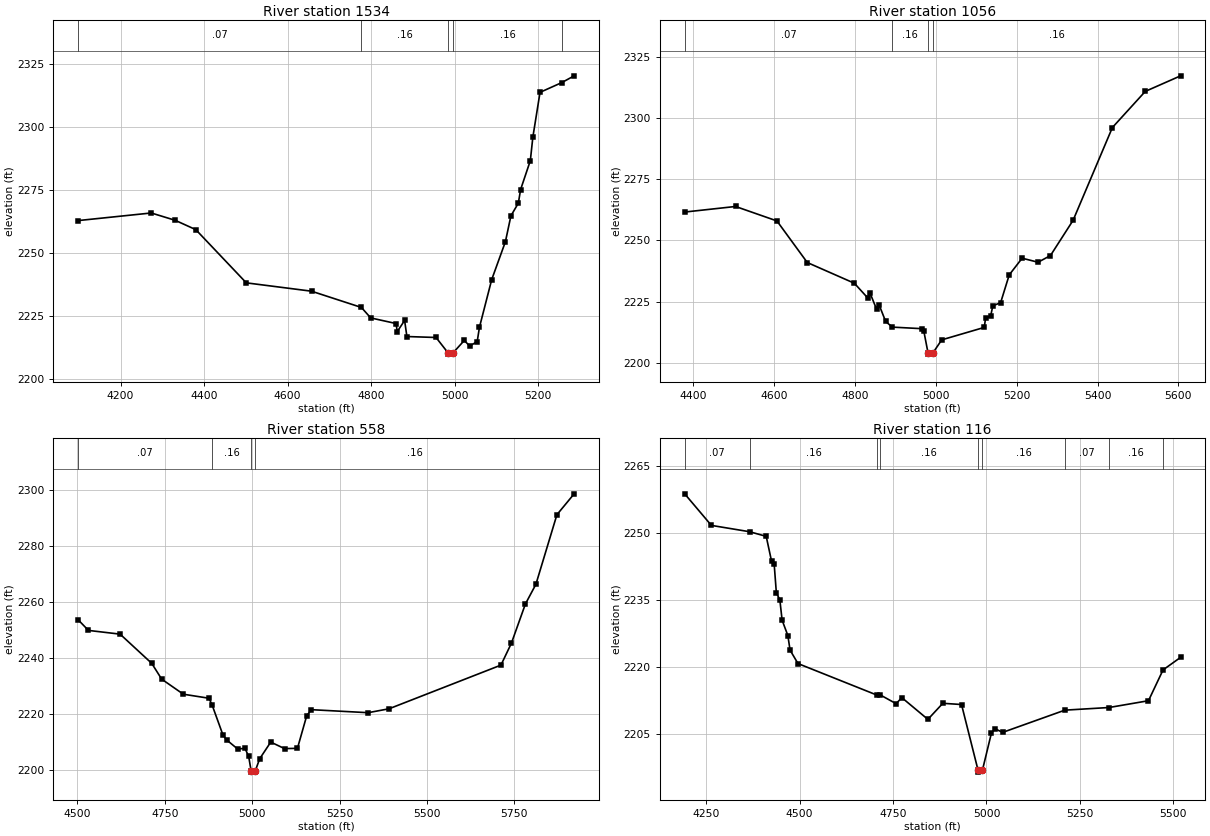
Type RM Length L Ch R = 1,1534,478,478,478
BEGIN DESCRIPTION:
elmc283
END DESCRIPTION:
XS GIS Cut Line= 3
      1492829.20      6783169.01      1493319.69      6782587.15
      1493492.82      6782197.61
#Sta/Elev= 30
  4098.7 2262.88  4273.6 2265.90  4330.8 2262.99  4380.2 2259.27  4501.1 2238.10
  4657.2 2234.78  4776.7 2228.31  4798.9 2224.15  4859.7 2221.91  4862.4 2218.69
  4880.1 2223.13  4885.6 2216.74  4955.4 2216.36  4984.1 2210.24  4984.6 2209.74
  4996.1 2210.24  5022.9 2215.18  5036.1 2212.95  5053.9 2214.76  5059.3 2220.44
  5088.6 2239.38  5121.4 2254.46  5134.6 2264.76  5152.4 2269.83  5157.8 2275.22
  5181.1 2286.74  5187.1 2296.04  5204.3 2313.90  5256.4 2317.78  5286.0 2320.47
#Mann=5,-1,0
  4098.7    0.07       0  4776.7    0.16       0  4984.1    0.07       0
  4996.1    0.16       0  5256.4    0.07       0
Bank Sta=4984.1,4996.1
Exp/Cntr=0.3,0.1

Type RM Length L Ch R = 1,1056,498,498,498
BEGIN DESCRIPTION:
elmc282
END DESCRIPTION:
XS GIS Cut Line= 3
      1492882.13      6783202.66      1493545.71      6782861.25
      1493709.19      6782409.26
#Sta/Elev= 30
  4378.6 2261.61  4504.5 2263.89  4606.8 2257.98  4681.9 2240.98  4798.4 2232.51
  4831.5 2226.50  4837.1 2228.52  4853.6 2221.79  4859.3 2223.79  4875.8 2216.89
  4892.3 2214.58  4964.5 2213.95  4970.1 2213.05  4980.6 2204.04  4981.1 2203.54
  4992.7 2204.04  5014.5 2209.37  5119.7 2214.46  5122.9 2218.18  5135.6 2219.17
  5140.9 2223.29  5160.2 2224.56  5181.5 2235.93  5213.4 2242.75  5252.8 2241.10
  5283.5 2243.83  5339.5 2258.24  5436.7 2296.16  5518.1 2310.93  5605.5 2317.29
#Mann=4,-1,0
  4378.6    0.07       0  4892.3    0.16       0  4980.6    0.07       0
  4992.7    0.16       0
Bank Sta=4980.6,4992.7
Exp/Cntr=0.3,0.1

Type RM Length L Ch R = 1,558,442,442,442
BEGIN DESCRIPTION:
elmc281
END DESCRIPTION:
XS GIS Cut Line= 4
      1493165.85      6783337.33      1493526.47      6783375.79
      1493843.85      6783270.00      1493824.62      6782548.67
#Sta/Elev= 30
  4502.3 2253.76  4531.6 2249.99  4622.1 2248.66  4712.6 2238.23  4741.1 2232.58
  4803.1 2227.20  4876.5 2225.76  4885.6 2223.26  4916.1 2212.73  4926.7 2210.90
  4958.3 2207.64  4979.4 2207.86  4989.9 2205.01  4996.9 2199.87  4997.4 2199.37
  5009.0 2199.87  5021.5 2204.15  5053.1 2210.10  5092.6 2207.77  5129.5 2207.87
  5155.8 2219.43  5169.1 2221.68  5331.6 2220.60  5391.6 2222.00  5711.7 2237.60
  5741.7 2245.46  5781.7 2259.45  5811.7 2266.47  5871.8 2291.33  5921.1 2298.78
#Mann=4,-1,0
  4502.3    0.07       0  4885.6    0.16       0  4996.9    0.07       0
  5009.0    0.16       0
Bank Sta=4996.9,5009
Exp/Cntr=0.3,0.1

Type RM Length L Ch R = 1,116,0,0,0
BEGIN DESCRIPTION:
elmc280
END DESCRIPTION:
XS GIS Cut Line= 4
      1493127.38      6783356.58      1493656.31      6783683.56
      1494002.54      6783669.13      1494276.63      6783438.32
#Sta/Elev= 30
  4192.6 2258.72  4264.0 2251.66  4366.5 2250.24  4410.7 2249.21  4424.9 2243.69
  4431.9 2243.12  4437.8 2236.63  4447.3 2234.94  4453.2 2230.47  4468.6 2227.03
  4474.5 2223.77  4495.7 2220.76  4707.8 2213.68  4715.5 2213.76  4758.2 2211.79
  4773.5 2213.14  4843.2 2208.28  4883.2 2211.87  4933.2 2211.60  4977.2 2196.98
  4977.7 2196.48  4989.3 2196.98  5013.3 2205.26  5023.3 2206.16  5043.3 2205.37
  5209.6 2210.34  5327.7 2210.93  5433.3 2212.45  5472.3 2219.34  5519.3 2222.15
#Mann=9,-1,0
  4192.6    0.07       0  4366.5    0.16       0  4707.8    0.07       0
  4715.5    0.16       0  4977.2    0.07       0  4989.3    0.16       0
  5209.6    0.07       0  5327.7    0.16       0  5472.3    0.07       0
Bank Sta=4977.2,4989.3
Exp/Cntr=0.3,0.1

Chan Stop Cuts=-1