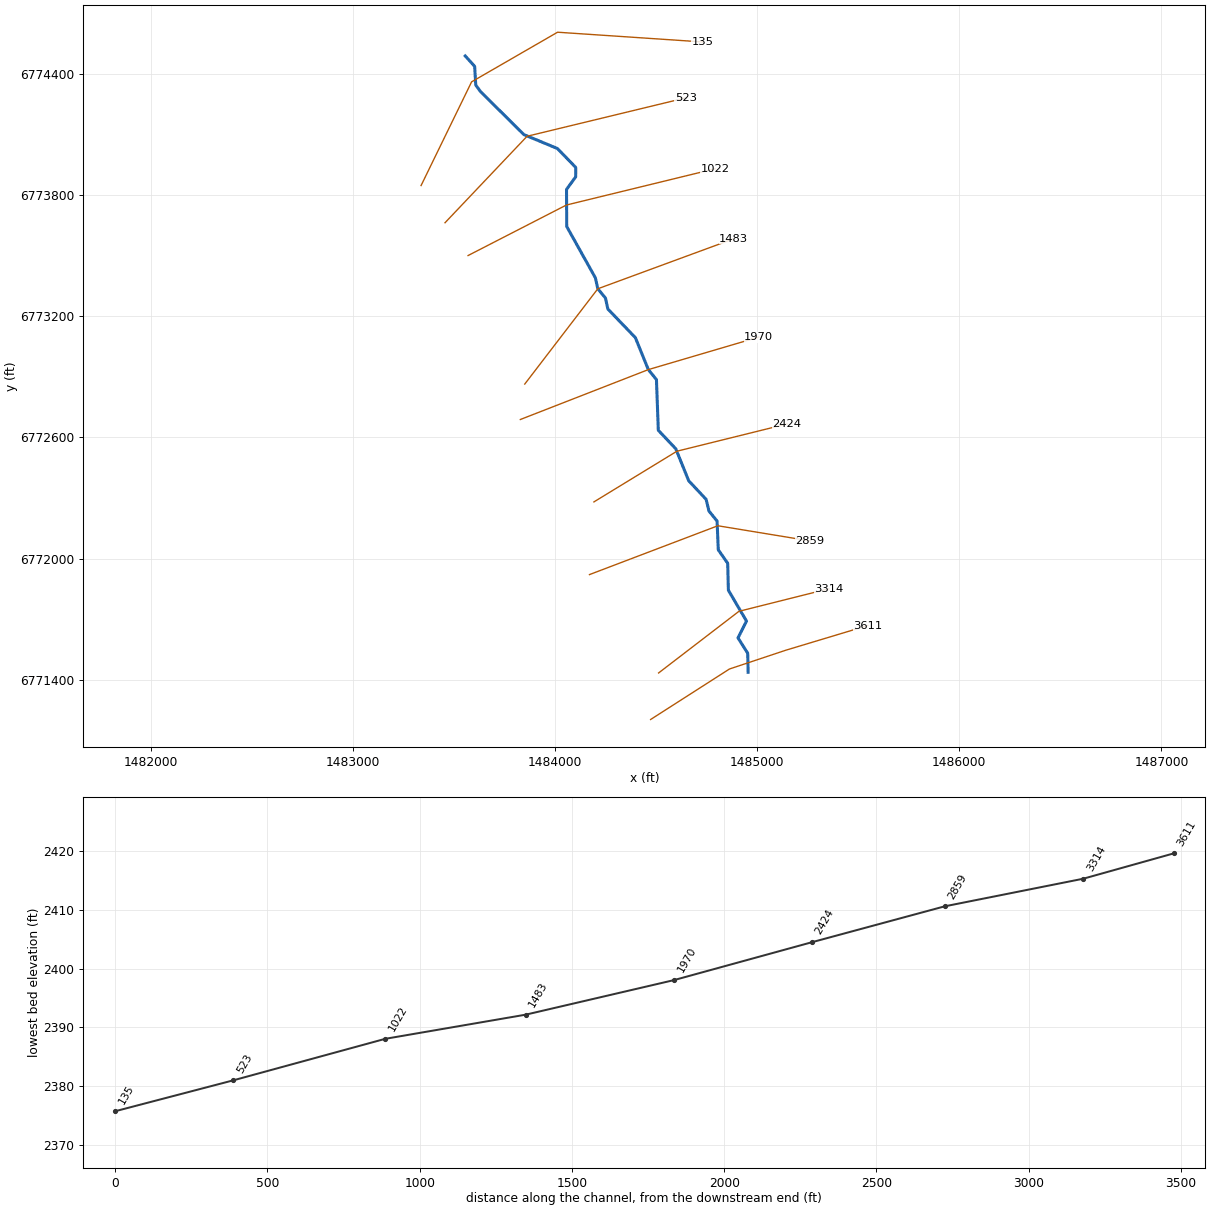
--- Elm 19.prj (project) ---

Proj Title=Elm 19 Base Level Engineering
Current Plan=p01
Default Exp/Contr=0.3,0.1
English Units
Geom File=g01
Flow File=f01
Plan File=p01
BEGIN DESCRIPTION:
Elm 19
END DESCRIPTION:

--- Elm 19.p01 (plan) ---

Plan Title=Multiple Run
Short Identifier=Multiple
Geom File=g01
Flow File=f01
Subcritical Flow
K Sum by GR= 0
Std Step Tol= 0.01
Critical Tol= 0.01
Num of Std Step Trials= 20
Max Error Tol= 0.3
Flow Tol Ratio= 0.001
Split Flow NTrial= 30
Split Flow Tol= 0.02
Split Flow Ratio= 0.02
Log Output Level= 0
Friction Slope Method= 1
Unsteady Friction Slope Method= 2
Unsteady Bridges Friction Slope Method= 1
Parabolic Critical Depth
Global Vel Dist=  1 , 1 , 1
Global Log Level= 0
CheckData=True
Encroach Param= -1, 0, 0, 0
BEGIN DESCRIPTION:
Multiple Run
END DESCRIPTION:

--- Elm 19.f01 (steady flow) ---

Flow Title=Multiple
Number of Profiles=7
Profile Names=10-year,25-year,50-year,1pct_min,100-year,1pct_plu,500-year
River Rch & RM= Elm 19,Reach-1,3611
     187     255     310     234     375     516     556
Boundary for River Rch & Prof#=Elm 19,Reach-1,1
Up Type=0
Dn Type=3
Dn Slope=0.005
Boundary for River Rch & Prof#=Elm 19,Reach-1,2
Up Type=0
Dn Type=3
Dn Slope=0.005
Boundary for River Rch & Prof#=Elm 19,Reach-1,3
Up Type=0
Dn Type=3
Dn Slope=0.005
Boundary for River Rch & Prof#=Elm 19,Reach-1,4
Up Type=0
Dn Type=3
Dn Slope=0.005
Boundary for River Rch & Prof#=Elm 19,Reach-1,5
Up Type=0
Dn Type=3
Dn Slope=0.005
Boundary for River Rch & Prof#=Elm 19,Reach-1,6
Up Type=0
Dn Type=3
Dn Slope=0.005
Boundary for River Rch & Prof#=Elm 19,Reach-1,7
Up Type=0
Dn Type=3
Dn Slope=0.005

--- Elm 19.g01 (geometry) ---

Geom Title=Existing Conditions

River Reach=Elm 19,Reach-1
Reach XY= 30
      1484955.00      6771438.00      1484952.87      6771532.14
      1484904.78      6771608.21      1484946.93      6771691.31
      1484857.25      6771843.93      1484853.77      6771977.49
      1484807.27      6772043.94      1484801.24      6772186.44
      1484761.14      6772235.83      1484746.84      6772294.05
      1484660.85      6772385.71      1484596.84      6772544.05
      1484510.47      6772635.55      1484501.25      6772886.45
      1484461.12      6772935.82      1484396.86      6773094.06
      1484260.83      6773235.70      1484248.90      6773290.19
      1484211.08      6773335.80      1484198.92      6773390.20
      1484057.24      6773643.93      1484056.24      6773827.50
      1484101.66      6773889.75      1484101.88      6773936.38
      1484011.08      6774029.87      1483845.32      6774098.76
      1483631.18      6774311.13      1483607.11      6774343.88
      1483601.61      6774436.59      1483555.00      6774488.00

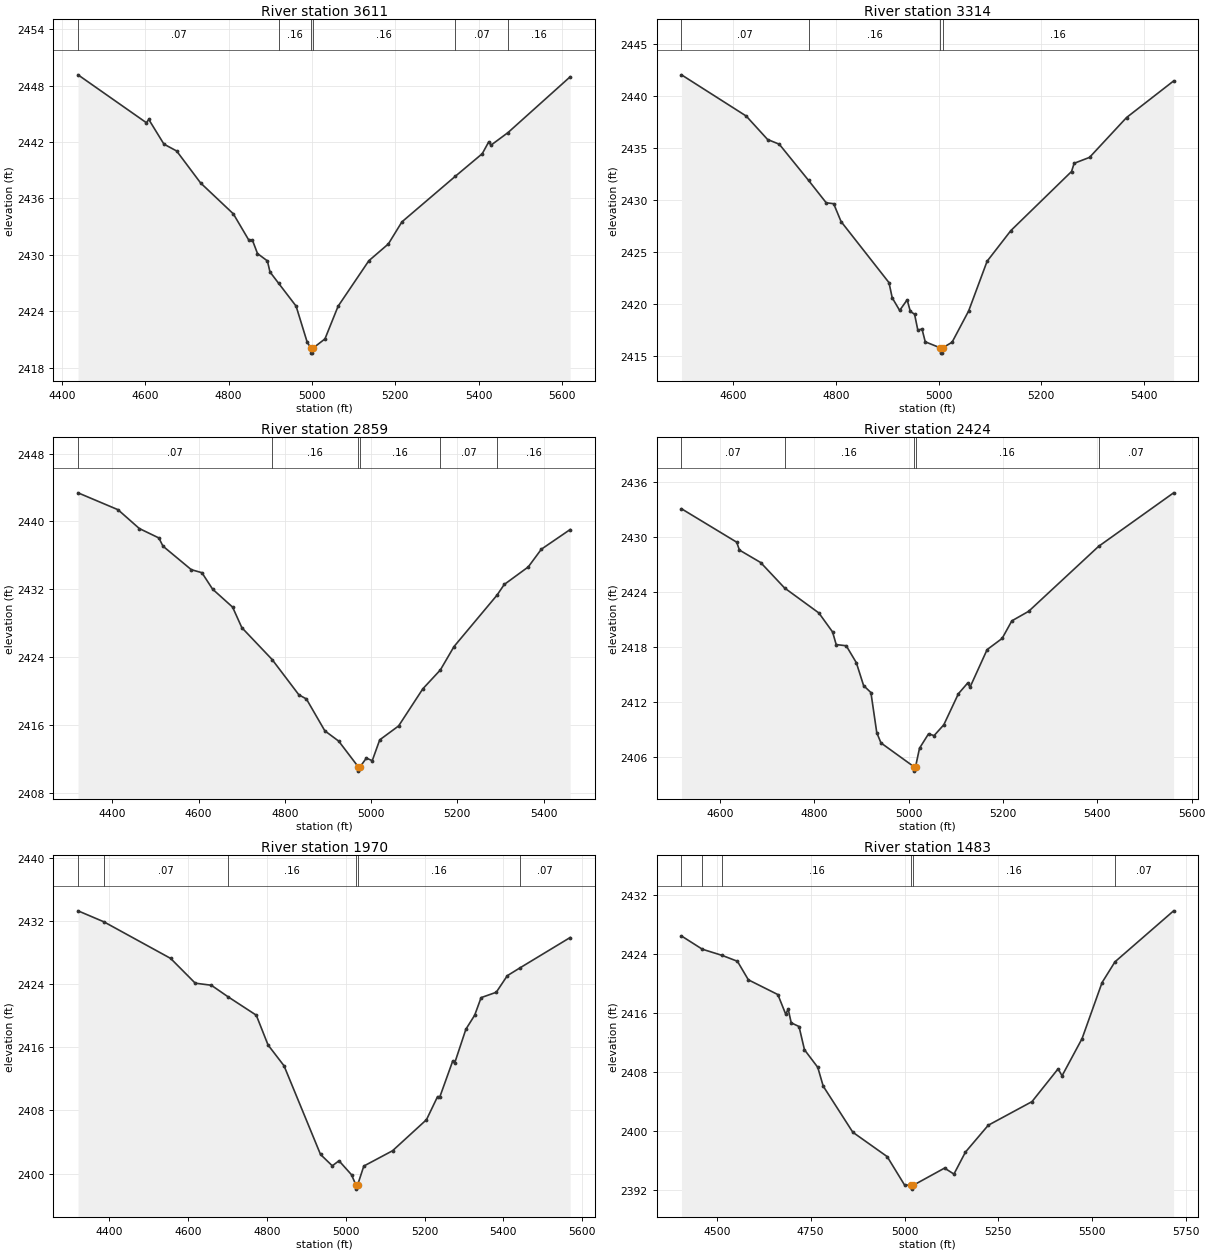
Type RM Length L Ch R = 1,3611,297,297,297
BEGIN DESCRIPTION:
elmc291
END DESCRIPTION:
XS GIS Cut Line= 4
      1484472.42      6771204.38      1484862.72      6771454.35
      1485139.01      6771546.44      1485546.90      6771669.25
#Sta/Elev= 30
  4438.8 2449.15  4602.7 2444.06  4608.6 2444.40  4644.9 2441.78  4675.4 2441.05
  4732.9 2437.65  4811.5 2434.36  4847.9 2431.62  4857.1 2431.58  4869.4 2430.14
  4893.1 2429.36  4899.4 2428.18  4920.4 2426.96  4962.0 2424.55  4988.3 2420.76
  4997.6 2420.05  4997.8 2419.55  5001.3 2419.55  5001.6 2420.05  5031.2 2421.06
  5062.8 2424.54  5136.6 2429.38  5183.3 2431.16  5215.9 2433.51  5343.5 2438.34
  5408.6 2440.76  5424.3 2442.03  5429.6 2441.67  5470.5 2443.01  5619.5 2448.94
#Mann=6,-1,0
  4438.8    0.07       0  4920.4    0.16       0  4997.6    0.07       0
  5001.6    0.16       0  5343.5    0.07       0  5470.5    0.16       0
Bank Sta=4997.6,5001.6
Exp/Cntr=0.3,0.1

Type RM Length L Ch R = 1,3314,455,455,455
BEGIN DESCRIPTION:
elmc194
END DESCRIPTION:
XS GIS Cut Line= 3
      1484511.86      6771434.60      1484909.42      6771739.64
      1485353.92      6771851.25
#Sta/Elev= 30
  4498.9 2442.05  4625.1 2438.08  4666.8 2435.82  4689.5 2435.37  4746.7 2431.88
  4781.0 2429.73  4795.5 2429.64  4810.0 2427.92  4903.4 2422.04  4909.7 2420.58
  4924.2 2419.36  4938.8 2420.38  4945.1 2419.26  4953.3 2419.00  4959.6 2417.47
  4967.8 2417.57  4974.1 2416.34  5003.8 2415.75  5004.0 2415.25  5007.5 2415.25
  5007.8 2415.75  5026.4 2416.30  5058.7 2419.31  5094.7 2424.10  5141.0 2427.05
  5259.3 2432.74  5264.4 2433.53  5294.4 2434.10  5366.6 2437.94  5458.3 2441.46
#Mann=4,-1,0
  4498.9    0.07       0  4746.7    0.16       0  5003.8    0.07       0
  5007.8    0.16       0
Bank Sta=5003.8,5007.8
Exp/Cntr=0.3,0.1

Type RM Length L Ch R = 1,2859,435,435,435
BEGIN DESCRIPTION:
elmc193
END DESCRIPTION:
XS GIS Cut Line= 3
      1484169.79      6771921.41      1484805.19      6772163.08
      1485260.88      6772088.22
#Sta/Elev= 30
  4320.2 2443.38  4412.9 2441.39  4462.4 2439.17  4507.7 2438.06  4517.3 2437.09
  4582.9 2434.32  4607.6 2433.96  4632.4 2432.02  4678.8 2429.90  4700.2 2427.48
  4770.5 2423.72  4832.5 2419.56  4850.0 2419.07  4892.8 2415.31  4924.9 2414.10
  4970.4 2411.06  4970.6 2410.56  4974.4 2411.06  4989.1 2412.10  5002.7 2411.79
  5020.1 2414.25  5063.9 2415.89  5120.1 2420.27  5160.7 2422.49  5192.4 2425.25
  5292.1 2431.31  5308.9 2432.57  5364.6 2434.64  5395.0 2436.73  5461.8 2439.05
#Mann=6,-1,0
  4320.2    0.07       0  4770.5    0.16       0  4970.4    0.07       0
  4974.4    0.16       0  5160.7    0.07       0  5292.1    0.16       0
Bank Sta=4970.4,4974.4
Exp/Cntr=0.3,0.1

Type RM Length L Ch R = 1,2424,454,454,454
BEGIN DESCRIPTION:
elmc192
END DESCRIPTION:
XS GIS Cut Line= 3
      1484191.76      6772281.06      1484602.49      6772531.96
      1485147.83      6772666.98
#Sta/Elev= 30
  4518.7 2433.13  4635.7 2429.48  4641.5 2428.62  4686.5 2427.26  4737.2 2424.48
  4809.9 2421.75  4838.9 2419.68  4846.6 2418.30  4867.9 2418.17  4889.3 2416.32
  4904.7 2413.82  4920.2 2413.06  4932.6 2408.68  4941.5 2407.56  5010.9 2404.98
  5011.1 2404.48  5014.9 2404.98  5023.2 2406.98  5042.3 2408.55  5054.1 2408.36
  5074.7 2409.54  5105.6 2412.93  5125.1 2414.09  5130.3 2413.65  5166.5 2417.75
  5198.3 2418.97  5218.9 2420.89  5254.5 2421.93  5402.7 2429.02  5561.8 2434.87
#Mann=5,-1,0
  4518.7    0.07       0  4737.2    0.16       0  5010.9    0.07       0
  5014.9    0.16       0  5402.7    0.07       0
Bank Sta=5010.9,5014.9
Exp/Cntr=0.3,0.1

Type RM Length L Ch R = 1,1970,487,487,487
BEGIN DESCRIPTION:
elmc191
END DESCRIPTION:
XS GIS Cut Line= 3
      1483827.74      6772688.91      1484461.12      6772935.82
      1485007.41      6773096.75
#Sta/Elev= 30
  4320.2 2433.26  4385.8 2431.87  4555.2 2427.24  4617.8 2424.10  4658.6 2423.84
  4701.0 2422.38  4772.7 2420.05  4802.6 2416.28  4843.2 2413.64  4935.8 2402.42
  4965.7 2400.98  4982.7 2401.62  5014.5 2399.85  5025.8 2398.53  5026.0 2398.03
  5029.8 2398.53  5045.7 2400.95  5118.7 2402.89  5204.8 2406.82  5233.0 2409.75
  5238.2 2409.64  5271.5 2414.26  5276.7 2414.04  5304.8 2418.27  5327.2 2420.05
  5343.4 2422.27  5381.9 2422.95  5410.0 2425.05  5441.5 2426.02  5569.5 2429.88
#Mann=6,-1,0
  4320.2    0.16       0  4385.8    0.07       0  4701.0    0.16       0
  5025.8    0.07       0  5029.8    0.16       0  5441.5    0.07       0
Bank Sta=5025.8,5029.8
Exp/Cntr=0.3,0.1

Type RM Length L Ch R = 1,1483,461,461,461
BEGIN DESCRIPTION:
elmc190
END DESCRIPTION:
XS GIS Cut Line= 3
      1483849.63      6772864.31      1484211.08      6773335.80
      1484883.91      6773583.29
#Sta/Elev= 30
  4405.9 2426.47  4461.3 2424.68  4514.7 2423.83  4554.9 2423.04  4584.0 2420.53
  4662.6 2418.53  4683.7 2415.85  4690.0 2416.58  4698.2 2414.70  4719.0 2414.20
  4733.5 2411.05  4768.9 2408.67  4783.4 2406.12  4862.3 2399.87  4953.8 2396.57
  5000.0 2392.73  5018.5 2392.66  5018.8 2392.16  5022.5 2392.66  5106.6 2395.01
  5131.7 2394.20  5162.2 2397.17  5223.1 2400.82  5339.6 2404.02  5409.1 2408.46
  5419.7 2407.52  5473.0 2412.56  5526.3 2420.16  5560.7 2422.97  5716.9 2429.88
#Mann=6,-1,0
  4405.9    0.16       0  4461.3    0.07       0  4514.7    0.16       0
  5018.5    0.07       0  5022.5    0.16       0  5560.7    0.07       0
Bank Sta=5018.5,5022.5
Exp/Cntr=0.3,0.1

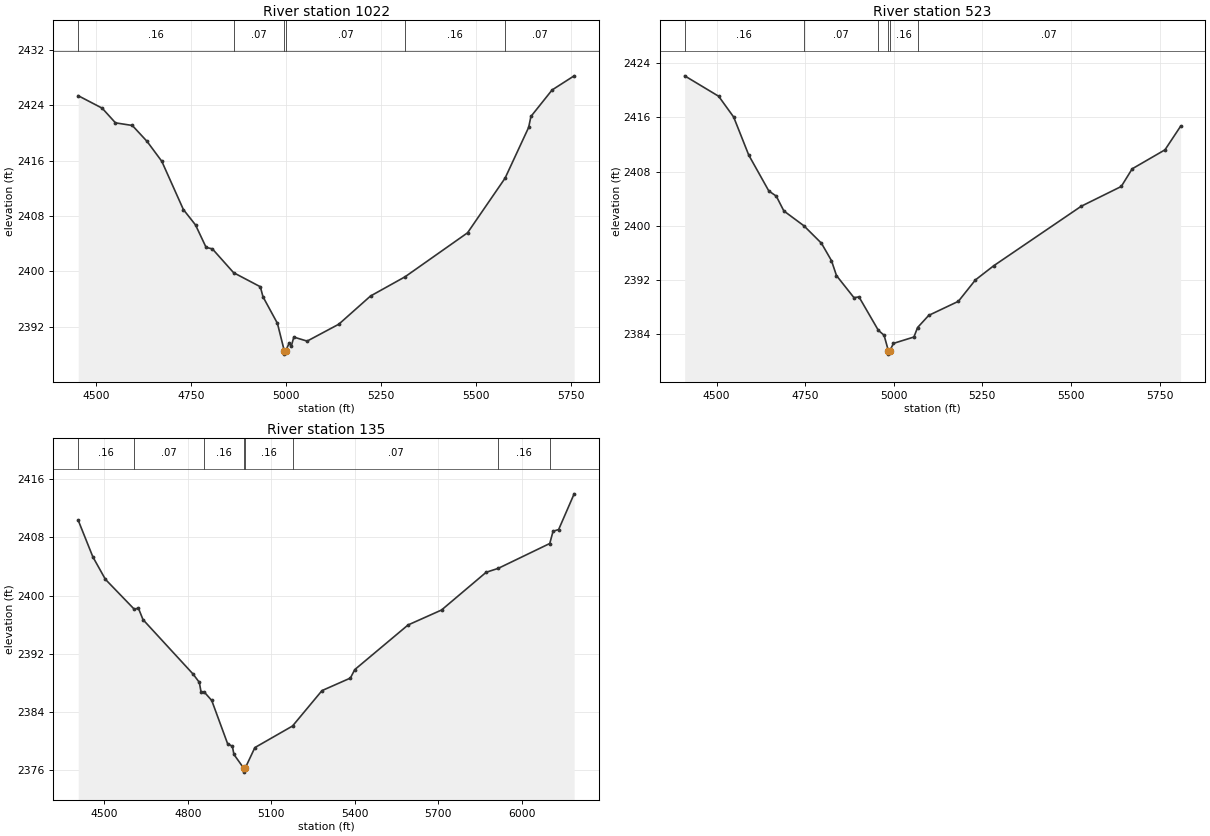
Type RM Length L Ch R = 1,1022,499,499,499
BEGIN DESCRIPTION:
elmc189
END DESCRIPTION:
XS GIS Cut Line= 3
      1483568.95      6773500.23      1484055.40      6773750.16
      1484791.31      6773929.73
#Sta/Elev= 30
  4453.1 2425.38  4516.1 2423.58  4551.1 2421.46  4595.4 2421.08  4634.2 2418.78
  4672.9 2415.91  4729.7 2408.94  4761.7 2406.71  4789.5 2403.47  4806.0 2403.26
  4861.8 2399.82  4932.1 2397.79  4939.1 2396.34  4977.1 2392.50  4995.0 2388.56
  4995.2 2388.06  4999.0 2388.56  5008.4 2389.70  5013.5 2389.21  5020.2 2390.52
  5055.2 2389.94  5138.5 2392.38  5221.9 2396.45  5312.8 2399.23  5477.1 2405.58
  5575.8 2413.47  5637.8 2420.80  5643.8 2422.38  5699.5 2426.21  5757.5 2428.25
#Mann=6,-1,0
  4453.1    0.16       0  4861.8    0.07       0  4995.0    0.07       0
  4999.0    0.07       0  5312.8    0.16       0  5575.8    0.07       0
Bank Sta=4995,4999
Exp/Cntr=0.3,0.1

Type RM Length L Ch R = 1,523,388,388,388
BEGIN DESCRIPTION:
elmc188
END DESCRIPTION:
XS GIS Cut Line= 3
      1483454.93      6773662.50      1483861.04      6774090.50
      1484647.83      6774280.88
#Sta/Elev= 30
  4410.0 2422.16  4505.9 2419.14  4548.3 2416.06  4590.8 2410.44  4647.4 2405.14
  4668.5 2404.37  4689.9 2402.18  4746.4 2399.99  4795.9 2397.41  4824.2 2394.84
  4838.4 2392.62  4887.7 2389.36  4901.9 2389.47  4956.4 2384.54  4972.7 2383.80
  4984.8 2381.51  4985.1 2381.01  4988.8 2381.51  4999.2 2382.60  5056.9 2383.54
  5067.2 2384.94  5098.7 2386.74  5182.4 2388.82  5230.4 2391.98  5281.9 2394.07
  5528.8 2402.87  5642.0 2405.80  5672.8 2408.41  5765.4 2411.22  5809.5 2414.71
#Mann=6,-1,0
  4410.0    0.16       0  4746.4    0.07       0  4956.4    0.16       0
  4984.8    0.07       0  4988.8    0.16       0  5067.2    0.07       0
Bank Sta=4984.8,4988.8
Exp/Cntr=0.3,0.1

Type RM Length L Ch R = 1,135,0,0,0
BEGIN DESCRIPTION:
elmc290
END DESCRIPTION:
XS GIS Cut Line= 4
      1483336.52      6773846.69      1483586.50      6774359.82
      1484011.91      6774605.42      1484730.60      6774557.21
#Sta/Elev= 30
  4406.4 2410.33  4459.0 2405.31  4504.0 2402.23  4608.6 2398.09  4622.3 2398.30
  4639.3 2396.69  4819.4 2389.21  4841.7 2388.08  4847.7 2386.79  4858.7 2386.78
  4886.2 2385.60  4943.4 2379.65  4960.4 2379.31  4966.0 2378.19  5001.9 2376.26
  5002.2 2375.76  5005.9 2376.26  5041.3 2379.13  5176.6 2382.09  5282.5 2386.95
  5384.5 2388.67  5400.2 2389.83  5591.8 2395.96  5712.0 2398.01  5872.4 2403.19
  5915.9 2403.73  6101.0 2407.14  6112.9 2408.82  6133.0 2409.06  6188.7 2413.96
#Mann=8,-1,0
  4406.4    0.16       0  4608.6    0.07       0  4858.7    0.16       0
  5001.9    0.07       0  5005.9    0.16       0  5176.6    0.07       0
  5915.9    0.16       0  6101.0    0.07       0
Bank Sta=5001.9,5005.9
Exp/Cntr=0.3,0.1

Chan Stop Cuts=-1