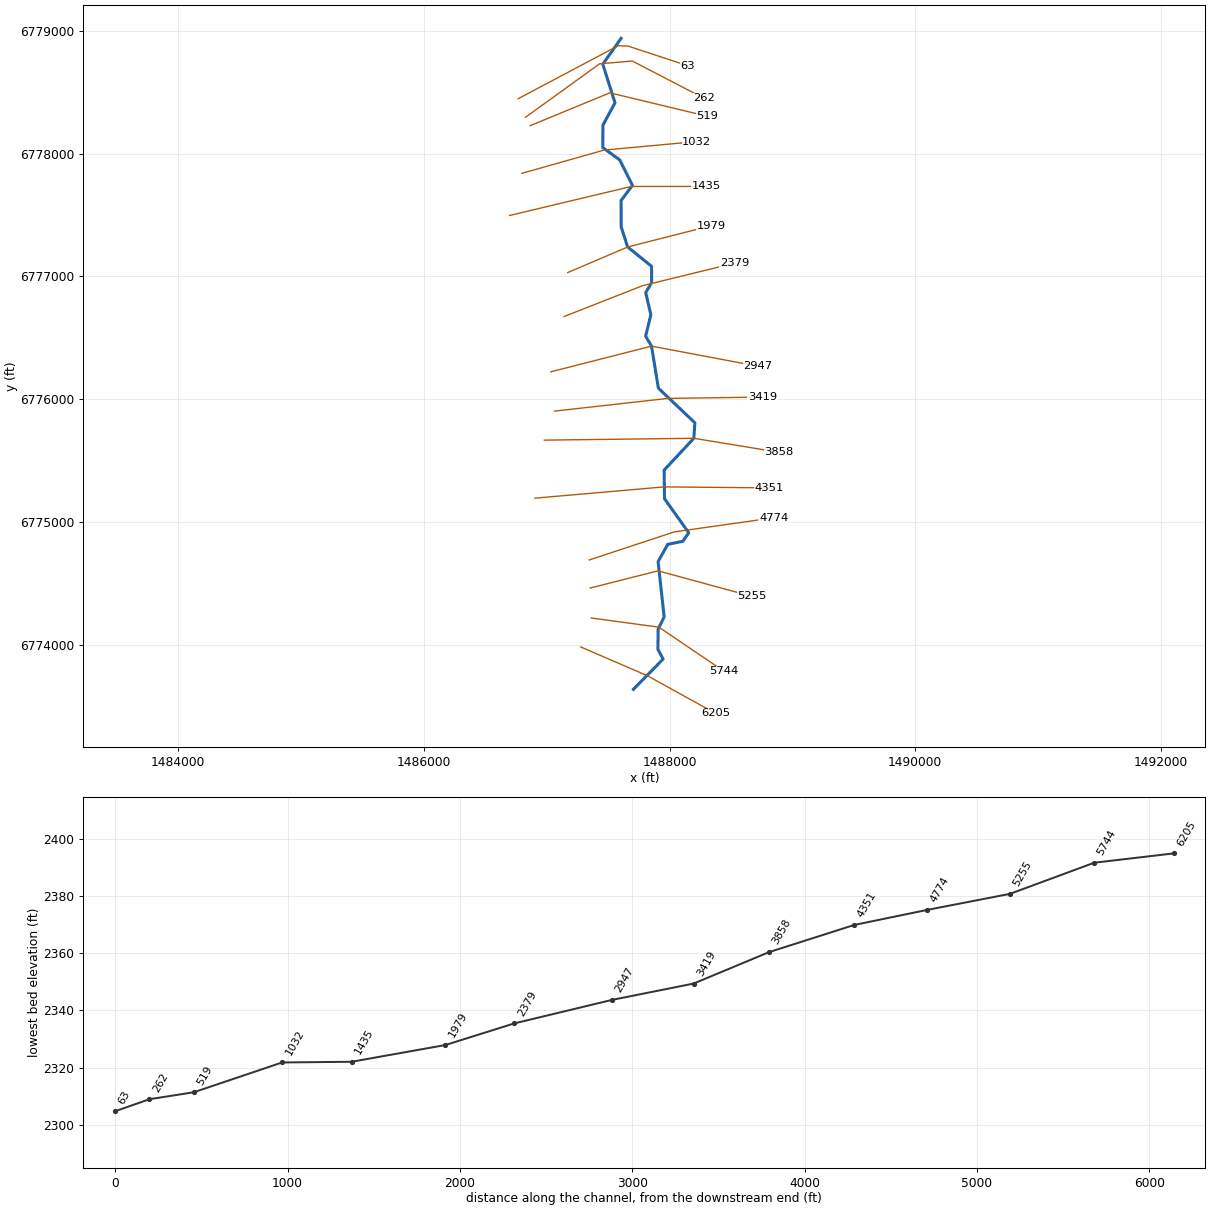
--- Elm 20.prj (project) ---

Proj Title=Elm 20 Base Level Engineering
Current Plan=p01
Default Exp/Contr=0.3,0.1
English Units
Geom File=g01
Flow File=f01
Plan File=p01
BEGIN DESCRIPTION:
Elm 20
END DESCRIPTION:

--- Elm 20.p01 (plan) ---

Plan Title=Multiple Run
Short Identifier=Multiple
Geom File=g01
Flow File=f01
Subcritical Flow
K Sum by GR= 0
Std Step Tol= 0.01
Critical Tol= 0.01
Num of Std Step Trials= 20
Max Error Tol= 0.3
Flow Tol Ratio= 0.001
Split Flow NTrial= 30
Split Flow Tol= 0.02
Split Flow Ratio= 0.02
Log Output Level= 0
Friction Slope Method= 1
Unsteady Friction Slope Method= 2
Unsteady Bridges Friction Slope Method= 1
Parabolic Critical Depth
Global Vel Dist=  1 , 1 , 1
Global Log Level= 0
CheckData=True
Encroach Param= -1, 0, 0, 0
BEGIN DESCRIPTION:
Multiple Run
END DESCRIPTION:

--- Elm 20.f01 (steady flow) ---

Flow Title=Multiple
Number of Profiles=7
Profile Names=10-year,25-year,50-year,1pct_min,100-year,1pct_plu,500-year
River Rch & RM= Elm 20,Reach-1,6205
     245     341     420     321     515     709     782
River Rch & RM= Elm 20,Reach-1,3419
     360     513     644     500     802    1100    1260
Boundary for River Rch & Prof#=Elm 20,Reach-1,1
Up Type=0
Dn Type=3
Dn Slope=0.005
Boundary for River Rch & Prof#=Elm 20,Reach-1,2
Up Type=0
Dn Type=3
Dn Slope=0.005
Boundary for River Rch & Prof#=Elm 20,Reach-1,3
Up Type=0
Dn Type=3
Dn Slope=0.005
Boundary for River Rch & Prof#=Elm 20,Reach-1,4
Up Type=0
Dn Type=3
Dn Slope=0.005
Boundary for River Rch & Prof#=Elm 20,Reach-1,5
Up Type=0
Dn Type=3
Dn Slope=0.005
Boundary for River Rch & Prof#=Elm 20,Reach-1,6
Up Type=0
Dn Type=3
Dn Slope=0.005
Boundary for River Rch & Prof#=Elm 20,Reach-1,7
Up Type=0
Dn Type=3
Dn Slope=0.005

--- Elm 20.g01 (geometry) ---

Geom Title=Existing Conditions

River Reach=Elm 20,Reach-1
Reach XY= 30
      1487705.00      6773638.00      1487947.21      6773884.58
      1487904.89      6773962.88      1487906.22      6774127.49
      1487955.46      6774227.82      1487906.20      6774677.50
      1487984.46      6774818.53      1488107.75      6774843.42
      1488155.63      6774912.91      1487958.55      6775189.47
      1487955.38      6775422.84      1488197.19      6775681.81
      1488205.47      6775808.17      1487908.61      6776089.50
      1487852.74      6776432.06      1487804.77      6776512.93
      1487847.44      6776688.00      1487805.05      6776867.96
      1487853.79      6776948.51      1487852.96      6777082.15
      1487658.52      6777239.28      1487605.52      6777403.22
      1487604.97      6777618.02      1487697.16      6777741.23
      1487594.37      6777948.00      1487455.98      6778048.28
      1487457.24      6778232.07      1487555.41      6778413.00
      1487455.93      6778727.52      1487605.00      6778938.00

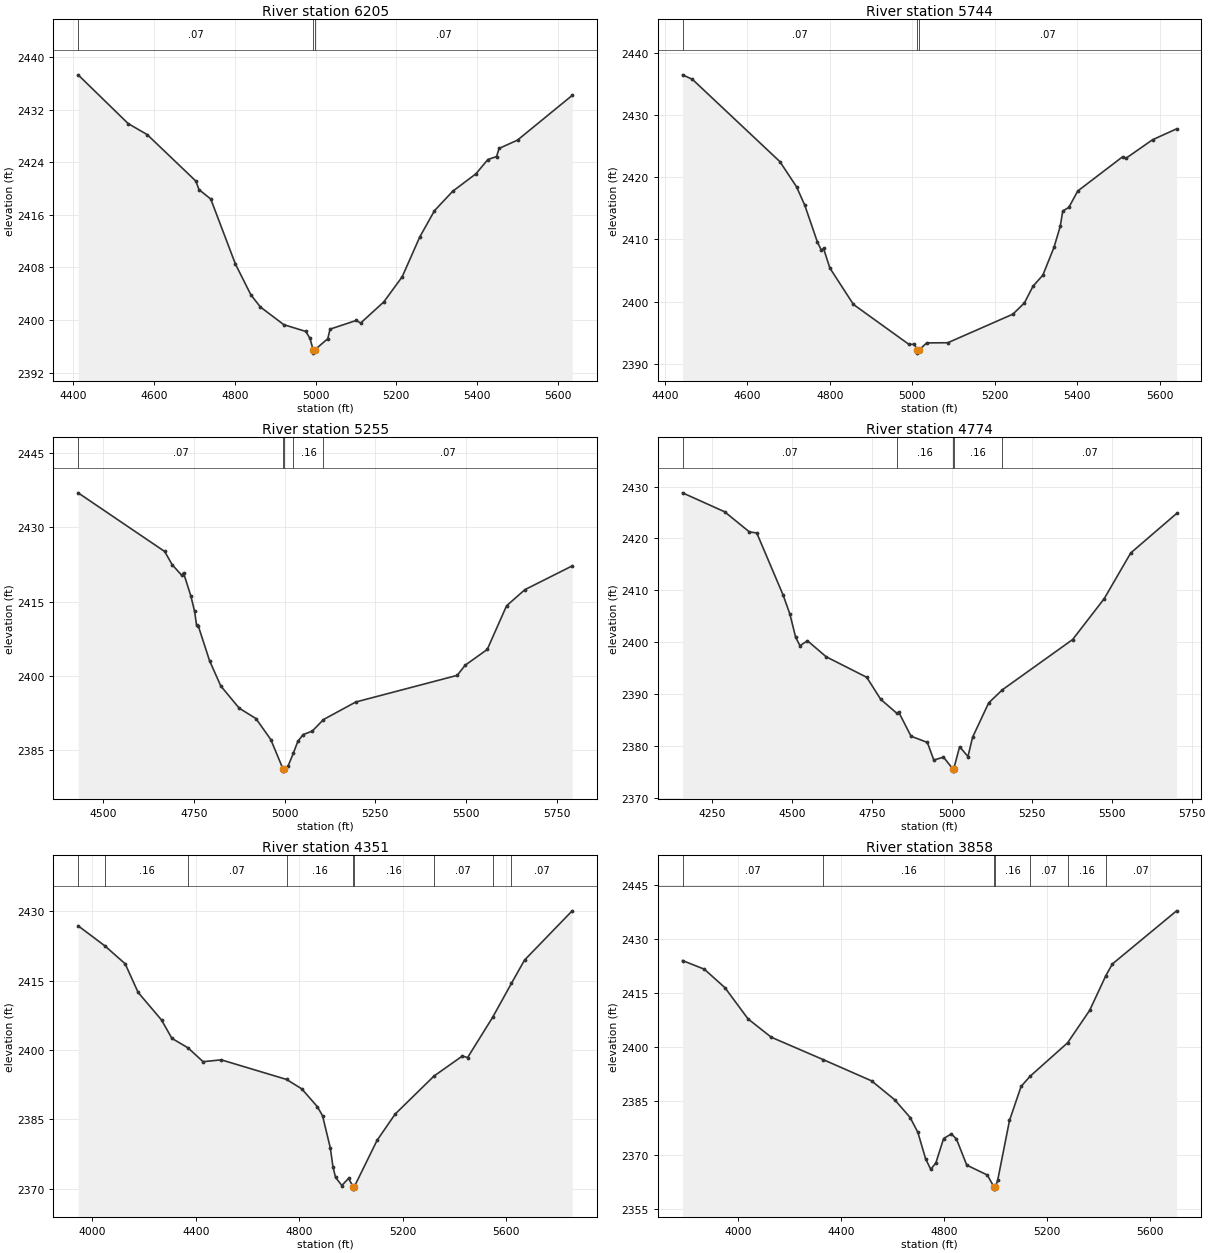
Type RM Length L Ch R = 1,6205,461,461,461
BEGIN DESCRIPTION:
elmc180
END DESCRIPTION:
XS GIS Cut Line= 3
      1487277.39      6773982.66      1487817.14      6773749.66
      1488373.48      6773442.30
#Sta/Elev= 30
  4412.1 2437.29  4536.1 2429.87  4583.1 2428.20  4703.6 2421.13  4711.5 2419.82
  4740.5 2418.40  4801.6 2408.51  4840.0 2403.81  4863.5 2401.97  4921.4 2399.28
  4975.9 2398.25  4986.4 2397.18  4994.1 2395.45  4994.4 2394.95  4998.1 2395.45
  5030.3 2397.14  5036.0 2398.60  5101.3 2399.93  5111.6 2399.52  5168.9 2402.73
  5214.6 2406.56  5258.3 2412.64  5294.6 2416.62  5339.6 2419.57  5397.4 2422.24
  5426.7 2424.40  5448.4 2424.86  5454.5 2426.09  5500.2 2427.36  5635.6 2434.16
#Mann=3,-1,0
  4412.1    0.07       0  4994.1    0.07       0  4998.1    0.07       0
Bank Sta=4994.1,4998.1
Exp/Cntr=0.3,0.1

Type RM Length L Ch R = 1,5744,489,489,489
BEGIN DESCRIPTION:
elmc179
END DESCRIPTION:
XS GIS Cut Line= 3
      1487361.20      6774218.92      1487913.14      6774144.06
      1488443.34      6773784.54
#Sta/Elev= 30
  4443.0 2436.51  4467.0 2435.78  4678.9 2422.54  4719.3 2418.49  4739.5 2415.48
  4769.8 2409.60  4779.7 2408.24  4784.8 2408.56  4800.0 2405.41  4857.3 2399.53
  4991.8 2393.10  5005.1 2393.11  5012.0 2392.19  5012.2 2391.69  5016.0 2392.19
  5035.0 2393.34  5085.9 2393.36  5243.9 2397.97  5271.6 2399.77  5292.6 2402.47
  5316.4 2404.25  5343.5 2408.74  5358.5 2412.10  5364.7 2414.58  5379.4 2415.16
  5401.0 2417.80  5509.7 2423.31  5517.2 2423.04  5582.2 2426.05  5640.6 2427.81
#Mann=3,-1,0
  4443.0    0.07       0  5012.0    0.07       0  5016.0    0.07       0
Bank Sta=5012,5016
Exp/Cntr=0.3,0.1

Type RM Length L Ch R = 1,5255,481,481,481
BEGIN DESCRIPTION:
elmc178
END DESCRIPTION:
XS GIS Cut Line= 3
      1487353.53      6774462.78      1487905.97      6774602.74
      1488671.03      6774394.46
#Sta/Elev= 30
  4430.1 2436.96  4668.9 2425.12  4689.5 2422.46  4715.7 2420.33  4720.8 2420.81
  4741.1 2416.13  4751.4 2413.03  4756.7 2410.28  4761.8 2410.04  4792.5 2403.11
  4823.6 2397.98  4874.5 2393.49  4920.6 2391.40  4961.6 2387.16  4994.9 2381.29
  4995.2 2380.79  4998.9 2381.29  5009.4 2381.85  5024.0 2384.45  5036.2 2386.81
  5050.8 2388.16  5075.9 2388.87  5106.9 2391.20  5195.9 2394.74  5475.7 2400.12
  5497.8 2402.17  5558.6 2405.35  5611.9 2414.16  5662.3 2417.41  5792.9 2422.21
#Mann=5,-1,0
  4430.1    0.07       0  4994.9    0.07       0  4998.9    0.07       0
  5024.0    0.16       0  5106.9    0.07       0
Bank Sta=4994.9,4998.9
Exp/Cntr=0.3,0.1

Type RM Length L Ch R = 1,4774,423,423,423
BEGIN DESCRIPTION:
elmc177
END DESCRIPTION:
XS GIS Cut Line= 3
      1487345.99      6774691.43      1488039.45      6774920.05
      1488847.23      6775034.35
#Sta/Elev= 30
  4156.9 2428.79  4288.6 2425.14  4366.4 2421.25  4389.1 2421.07  4471.7 2409.09
  4492.8 2405.44  4510.9 2400.95  4524.4 2399.34  4547.9 2400.29  4606.2 2397.21
  4733.3 2393.25  4777.1 2389.00  4827.7 2386.31  4833.8 2386.48  4871.9 2381.90
  4923.0 2380.70  4943.2 2377.30  4973.5 2377.87  5001.8 2375.67  5002.0 2375.17
  5005.8 2375.67  5024.0 2379.87  5050.1 2377.98  5064.4 2381.68  5114.9 2388.32
  5157.9 2390.85  5377.5 2400.52  5476.3 2408.39  5559.3 2417.20  5702.9 2424.81
#Mann=5,-1,0
  4156.9    0.07       0  4827.7    0.16       0  5001.8    0.07       0
  5005.8    0.16       0  5157.9    0.07       0
Bank Sta=5001.8,5005.8
Exp/Cntr=0.3,0.1

Type RM Length L Ch R = 1,4351,493,493,493
BEGIN DESCRIPTION:
elmc176
END DESCRIPTION:
XS GIS Cut Line= 3
      1486903.94      6775194.40      1487954.84      6775286.16
      1488809.20      6775278.23
#Sta/Elev= 30
  3945.1 2426.89  4048.4 2422.55  4126.9 2418.67  4177.0 2412.47  4267.4 2406.51
  4307.5 2402.53  4369.7 2400.48  4428.0 2397.48  4498.3 2397.88  4750.5 2393.64
  4809.4 2391.60  4869.7 2387.74  4889.7 2385.77  4919.9 2378.77  4929.9 2374.72
  4939.9 2372.45  4964.3 2370.68  4990.1 2372.23  5008.2 2370.40  5008.4 2369.90
  5012.2 2370.40  5100.2 2380.44  5170.2 2386.14  5320.3 2394.37  5430.2 2398.71
  5450.2 2398.37  5547.0 2407.09  5619.7 2414.44  5670.2 2419.47  5854.4 2430.13
#Mann=9,-1,0
  3945.1    0.07       0  4048.4    0.16       0  4369.7    0.07       0
  4750.5    0.16       0  5008.2    0.07       0  5012.2    0.16       0
  5320.3    0.07       0  5547.0    0.16       0  5619.7    0.07       0
Bank Sta=5008.2,5012.2
Exp/Cntr=0.3,0.1

Type RM Length L Ch R = 1,3858,439,439,439
BEGIN DESCRIPTION:
elmc175
END DESCRIPTION:
XS GIS Cut Line= 3
      1486980.19      6775666.90      1488197.19      6775681.81
      1488891.54      6775568.06
#Sta/Elev= 30
  3782.9 2424.09  3867.7 2421.68  3947.7 2416.54  4037.7 2407.83  4127.7 2402.74
  4330.6 2396.47  4517.8 2390.58  4607.8 2385.31  4667.8 2380.37  4697.8 2376.23
  4727.8 2368.89  4747.8 2365.93  4767.8 2367.73  4797.8 2374.51  4827.8 2375.80
  4847.8 2374.39  4887.8 2367.11  4967.8 2364.35  4994.4 2360.92  4994.7 2360.42
  4998.4 2360.92  5007.9 2362.83  5054.0 2379.54  5099.1 2389.03  5133.9 2391.85
  5279.8 2401.17  5365.7 2410.22  5428.4 2419.86  5453.8 2423.13  5703.6 2437.94
#Mann=7,-1,0
  3782.9    0.07       0  4330.6    0.16       0  4994.4    0.07       0
  4998.4    0.16       0  5133.9    0.07       0  5279.8    0.16       0
  5428.4    0.07       0
Bank Sta=4994.4,4998.4
Exp/Cntr=0.3,0.1

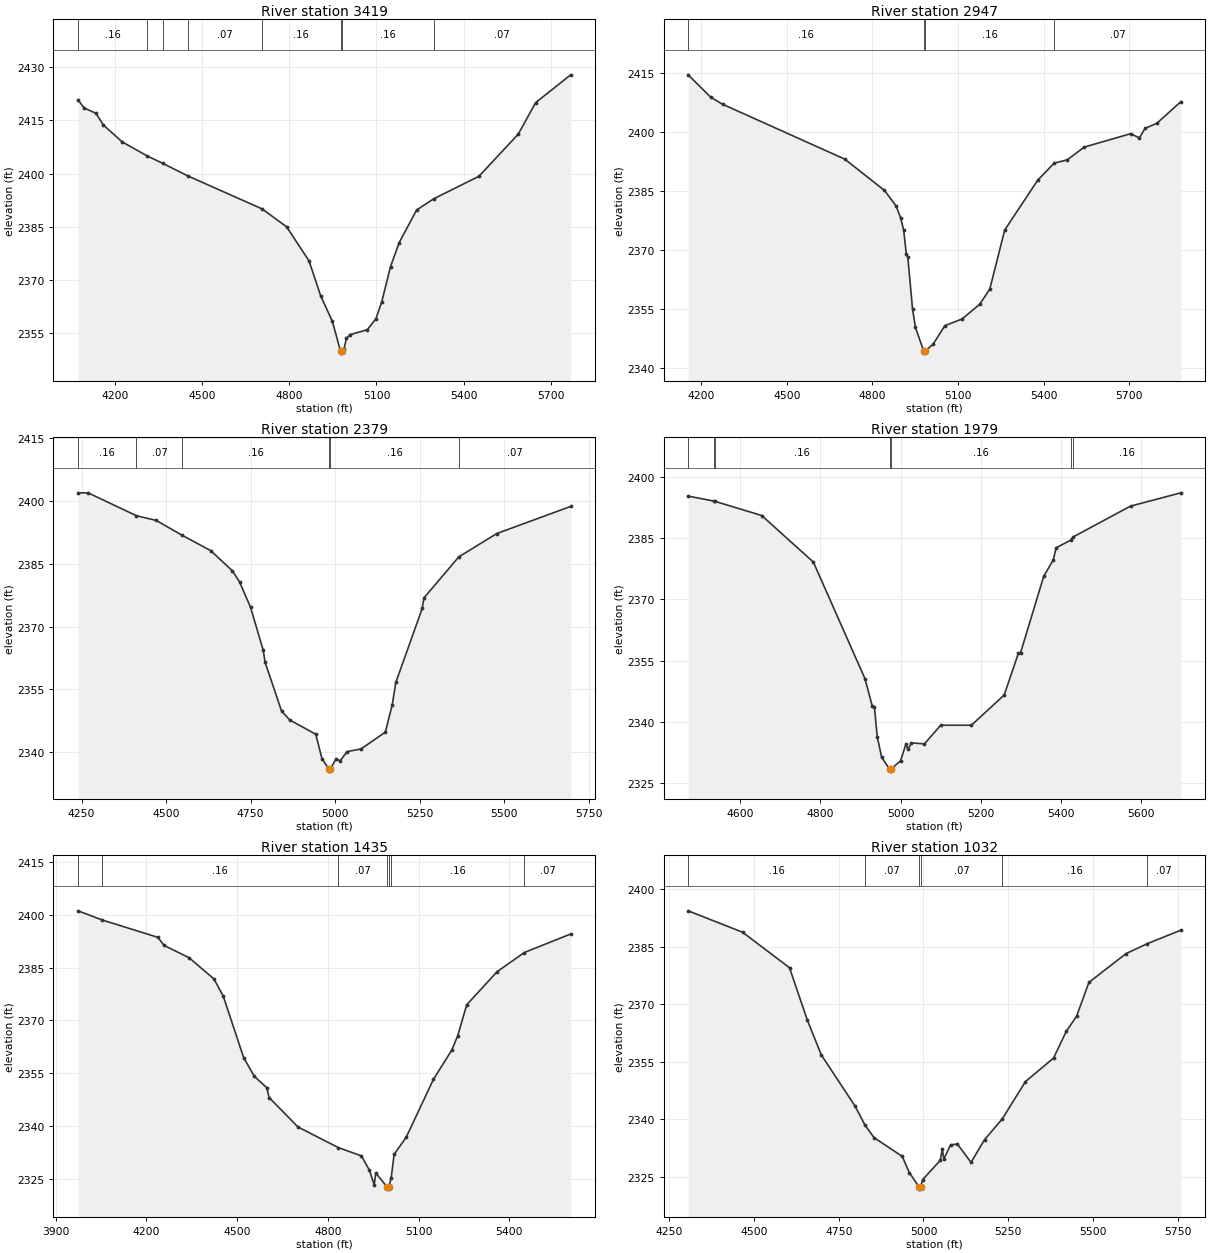
Type RM Length L Ch R = 1,3419,472,472,472
BEGIN DESCRIPTION:
elmc174
END DESCRIPTION:
XS GIS Cut Line= 3
      1487063.98      6775903.15      1487986.60      6776006.63
      1488755.82      6776017.46
#Sta/Elev= 30
  4071.6 2420.78  4092.7 2418.51  4133.0 2417.02  4159.1 2413.70  4223.6 2408.95
  4309.9 2404.99  4363.2 2402.91  4450.6 2399.33  4705.6 2390.07  4790.1 2385.03
  4867.6 2375.41  4907.8 2365.54  4948.1 2358.33  4976.3 2349.89  4976.5 2349.39
  4980.3 2349.89  4988.3 2350.67  4996.7 2353.57  5008.4 2354.58  5068.4 2355.99
  5098.4 2359.12  5118.4 2363.93  5148.4 2373.77  5178.4 2380.57  5238.4 2389.75
  5297.7 2392.93  5453.0 2399.24  5588.5 2411.12  5648.5 2420.01  5769.3 2427.86
#Mann=8,-1,0
  4071.6    0.16       0  4309.9    0.07       0  4363.2    0.16       0
  4450.6    0.07       0  4705.6    0.16       0  4976.3    0.07       0
  4980.3    0.16       0  5297.7    0.07       0
Bank Sta=4976.3,4980.3
Exp/Cntr=0.3,0.1

Type RM Length L Ch R = 1,2947,568,568,568
BEGIN DESCRIPTION:
elmc173
END DESCRIPTION:
XS GIS Cut Line= 3
      1487033.44      6776223.21      1487852.74      6776432.06
      1488717.69      6776268.95
#Sta/Elev= 30
  4154.5 2414.64  4234.1 2408.90  4274.9 2407.15  4703.1 2393.15  4842.1 2385.18
  4883.0 2381.21  4899.1 2378.13  4909.5 2375.01  4918.7 2369.00  4923.9 2368.17
  4940.4 2355.05  4950.7 2350.25  4979.7 2344.20  4979.9 2343.70  4983.7 2344.20
  5012.5 2345.96  5053.6 2350.69  5114.2 2352.41  5175.3 2356.12  5210.9 2359.97
  5263.3 2375.06  5378.8 2387.76  5436.6 2392.12  5483.1 2392.99  5541.6 2396.21
  5704.5 2399.63  5735.0 2398.57  5755.4 2401.01  5796.1 2402.27  5880.2 2407.78
#Mann=4,-1,0
  4154.5    0.16       0  4979.7    0.07       0  4983.7    0.16       0
  5436.6    0.07       0
Bank Sta=4979.7,4983.7
Exp/Cntr=0.3,0.1

Type RM Length L Ch R = 1,2379,400,400,400
BEGIN DESCRIPTION:
elmc172
END DESCRIPTION:
XS GIS Cut Line= 3
      1487140.13      6776672.84      1487780.33      6776924.35
      1488527.23      6777107.26
#Sta/Elev= 30
  4239.5 2401.96  4269.4 2401.95  4412.1 2396.49  4470.4 2395.37  4547.9 2391.79
  4631.5 2388.17  4696.0 2383.32  4717.5 2380.60  4749.7 2374.59  4787.1 2364.33
  4792.7 2361.45  4841.3 2349.82  4865.7 2347.67  4942.4 2344.29  4960.8 2338.44
  4981.6 2335.96  4981.9 2335.46  4985.6 2335.96  5002.4 2338.41  5014.5 2337.93
  5035.1 2340.12  5076.3 2340.76  5148.3 2344.78  5168.8 2351.38  5179.2 2356.64
  5257.2 2374.32  5262.4 2376.85  5365.4 2386.65  5477.8 2392.23  5696.3 2398.71
#Mann=6,-1,0
  4239.5    0.16       0  4412.1    0.07       0  4547.9    0.16       0
  4981.6    0.07       0  4985.6    0.16       0  5365.4    0.07       0
Bank Sta=4981.6,4985.6
Exp/Cntr=0.3,0.1

Type RM Length L Ch R = 1,1979,544,544,544
BEGIN DESCRIPTION:
elmc171
END DESCRIPTION:
XS GIS Cut Line= 3
      1487170.70      6777031.06      1487658.52      6777239.28
      1488336.65      6777412.08
#Sta/Elev= 30
  4469.6 2395.32  4534.1 2394.09  4535.6 2394.06  4653.3 2390.56  4782.2 2379.15
  4911.1 2350.56  4929.3 2343.86  4934.7 2343.65  4941.8 2336.33  4952.7 2331.32
  4972.4 2328.39  4972.7 2327.89  4976.4 2328.39  5000.0 2330.43  5013.5 2334.52
  5018.6 2333.22  5027.3 2334.82  5059.5 2334.56  5100.4 2339.15  5177.0 2339.15
  5258.8 2346.55  5294.5 2356.84  5299.7 2356.91  5357.5 2375.66  5381.4 2379.68
  5388.5 2382.64  5424.8 2384.52  5430.7 2385.29  5574.3 2392.86  5699.8 2396.12
#Mann=7,-1,0
  4469.6    0.16       0  4534.1    0.07       0  4535.6    0.16       0
  4972.4    0.07       0  4976.4    0.16       0  5424.8    0.07       0
  5430.7    0.16       0
Bank Sta=4972.4,4976.4
Exp/Cntr=0.3,0.1

Type RM Length L Ch R = 1,1435,403,403,403
BEGIN DESCRIPTION:
elmc170
END DESCRIPTION:
XS GIS Cut Line= 3
      1486698.17      6777495.92      1487688.88      6777732.16
      1488298.59      6777732.16
#Sta/Elev= 30
  3974.4 2401.14  4054.5 2398.53  4238.4 2393.60  4258.7 2391.31  4341.2 2387.82
  4423.5 2381.79  4454.3 2376.89  4521.7 2359.43  4557.1 2354.08  4598.2 2350.86
  4605.9 2348.06  4701.1 2339.71  4834.3 2333.85  4911.0 2331.48  4937.5 2327.41
  4953.2 2323.25  4958.3 2326.63  4997.0 2322.53  4997.2 2322.03  5001.1 2322.53
  5009.5 2325.31  5019.0 2331.89  5059.0 2336.78  5149.0 2353.24  5209.0 2361.45
  5229.0 2365.56  5259.0 2374.44  5359.0 2383.81  5449.5 2389.29  5602.6 2394.56
#Mann=7,-1,0
  3974.4    0.07       0  4054.5    0.16       0  4834.3    0.07       0
  4997.0    0.07       0  5001.1    0.07       0  5009.5    0.16       0
  5449.5    0.07       0
Bank Sta=4997,5001.1
Exp/Cntr=0.3,0.1

Type RM Length L Ch R = 1,1032,513,513,513
BEGIN DESCRIPTION:
elmc169
END DESCRIPTION:
XS GIS Cut Line= 3
      1486797.27      6777838.87      1487465.35      6778027.88
      1488221.21      6778097.86
#Sta/Elev= 30
  4305.7 2394.43  4466.1 2388.85  4604.7 2379.58  4656.7 2366.06  4698.3 2356.85
  4797.7 2343.52  4827.1 2338.55  4854.1 2335.23  4937.3 2330.34  4958.1 2326.13
  4987.2 2322.29  4987.4 2321.79  4991.3 2322.29  4997.2 2324.23  5049.9 2329.34
  5055.2 2332.21  5060.2 2329.68  5080.0 2333.36  5100.1 2333.54  5140.3 2328.77
  5180.4 2334.73  5232.2 2340.09  5300.9 2349.87  5383.6 2355.99  5421.4 2363.00
  5451.6 2366.91  5488.1 2375.75  5597.5 2383.26  5659.6 2385.83  5759.1 2389.37
#Mann=6,-1,0
  4305.7    0.16       0  4827.1    0.07       0  4987.2    0.07       0
  4991.3    0.07       0  5232.2    0.16       0  5659.6    0.07       0
Bank Sta=4987.2,4991.3
Exp/Cntr=0.3,0.1

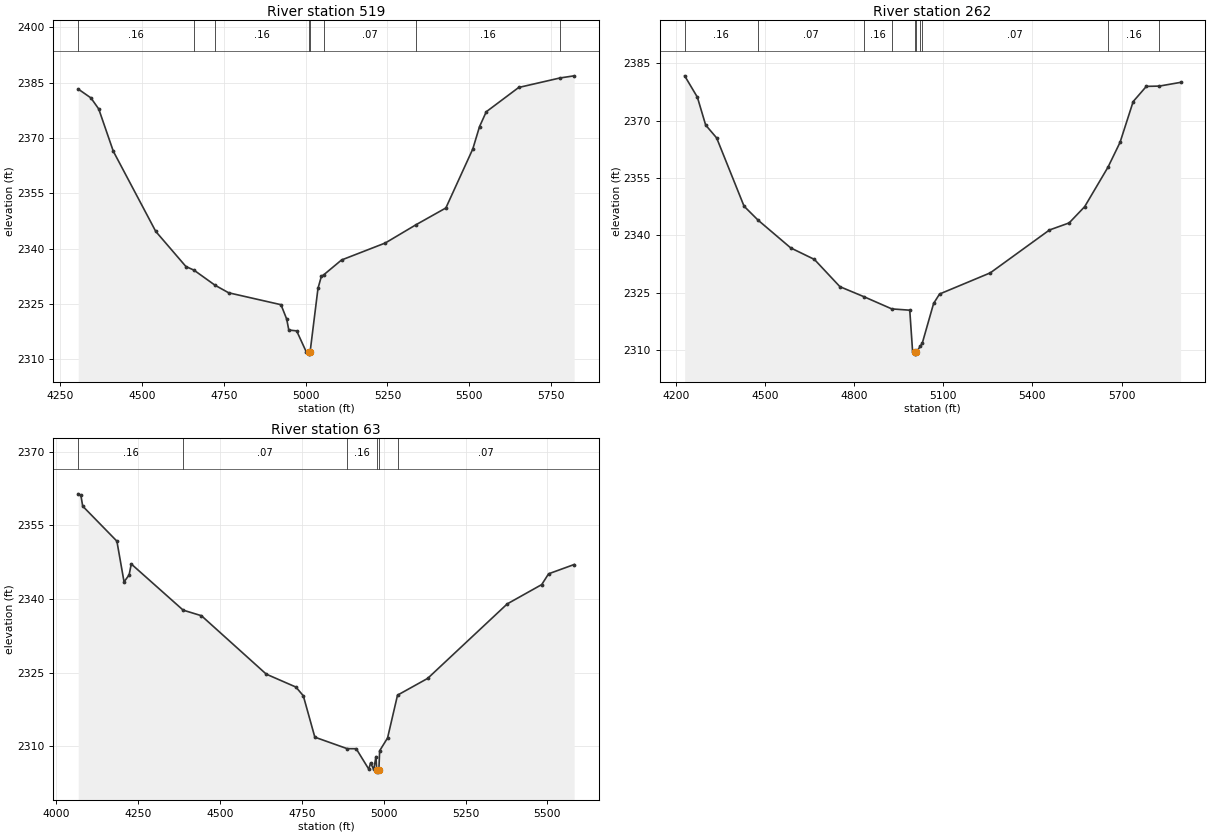
Type RM Length L Ch R = 1,519,257,257,257
BEGIN DESCRIPTION:
elmc168
END DESCRIPTION:
XS GIS Cut Line= 3
      1486865.84      6778227.53      1487513.60      6778494.25
      1488306.19      6778303.73
#Sta/Elev= 30
  4305.1 2383.27  4343.9 2380.87  4367.8 2377.87  4412.3 2366.41  4542.1 2344.65
  4634.3 2335.12  4658.8 2334.15  4723.3 2330.05  4764.9 2328.00  4924.8 2324.77
  4942.3 2320.86  4948.7 2317.89  4972.7 2317.67  5002.0 2311.99  5009.5 2311.86
  5009.8 2311.36  5013.7 2311.86  5037.9 2329.20  5048.2 2332.45  5056.6 2332.96
  5109.9 2336.90  5243.6 2341.51  5338.2 2346.50  5428.7 2351.01  5511.0 2367.01
  5531.6 2373.08  5552.2 2377.11  5651.3 2383.70  5777.5 2386.28  5820.8 2386.86
#Mann=8,-1,0
  4305.1    0.16       0  4658.8    0.07       0  4723.3    0.16       0
  5009.5    0.07       0  5013.7    0.16       0  5056.6    0.07       0
  5338.2    0.16       0  5777.5    0.07       0
Bank Sta=5009.5,5013.7
Exp/Cntr=0.3,0.1

Type RM Length L Ch R = 1,262,199,199,199
BEGIN DESCRIPTION:
elmc292
END DESCRIPTION:
XS GIS Cut Line= 4
      1486827.74      6778296.13      1487429.77      6778730.50
      1487696.50      6778753.37      1488281.67      6778449.38
#Sta/Elev= 30
  4229.5 2381.72  4272.3 2376.12  4300.1 2368.85  4337.1 2365.48  4429.4 2347.62
  4476.5 2343.98  4586.5 2336.71  4666.2 2333.70  4752.1 2326.57  4832.0 2323.98
  4926.7 2320.76  4987.2 2320.42  4996.6 2309.80  5005.1 2309.43  5005.4 2308.93
  5009.3 2309.43  5022.3 2310.96  5029.4 2311.81  5067.5 2322.19  5087.5 2324.65
  5258.4 2330.19  5457.5 2341.40  5523.8 2343.25  5576.0 2347.50  5654.6 2357.84
  5695.1 2364.32  5739.3 2374.99  5783.6 2378.96  5827.7 2379.04  5899.0 2380.01
#Mann=10,-1,0
  4229.5    0.16       0  4476.5    0.07       0  4832.0    0.16       0
  4926.7    0.07       0  5005.1    0.07       0  5009.3    0.07       0
  5022.3    0.16       0  5029.4    0.07       0  5654.6    0.16       0
  5827.7    0.07       0
Bank Sta=5005.1,5009.3
Exp/Cntr=0.3,0.1

Type RM Length L Ch R = 1,63,0,0,0
BEGIN DESCRIPTION:
elma819
END DESCRIPTION:
XS GIS Cut Line= 4
      1486767.59      6778446.72      1487581.89      6778878.22
      1487661.92      6778874.74      1488149.13      6778714.66
#Sta/Elev= 30
  4067.1 2361.41  4075.2 2361.12  4080.8 2358.90  4185.2 2351.77  4207.1 2343.47
  4222.6 2344.90  4229.1 2347.12  4387.5 2337.72  4443.4 2336.58  4641.4 2324.68
  4731.9 2322.05  4754.5 2320.27  4789.7 2311.84  4888.5 2309.50  4916.0 2309.49
  4954.4 2305.33  4960.0 2306.60  4969.5 2305.26  4976.4 2307.89  4978.8 2305.22
  4979.3 2304.72  4985.3 2305.22  4987.6 2309.07  5011.8 2311.68  5042.2 2320.40
  5134.2 2323.81  5377.3 2338.99  5482.5 2342.92  5503.6 2345.12  5581.6 2347.01
#Mann=6,-1,0
  4067.1    0.16       0  4387.5    0.07       0  4888.5    0.16       0
  4978.8    0.07       0  4985.3    0.16       0  5042.2    0.07       0
Bank Sta=4978.8,4985.3
Exp/Cntr=0.3,0.1

Chan Stop Cuts=-1