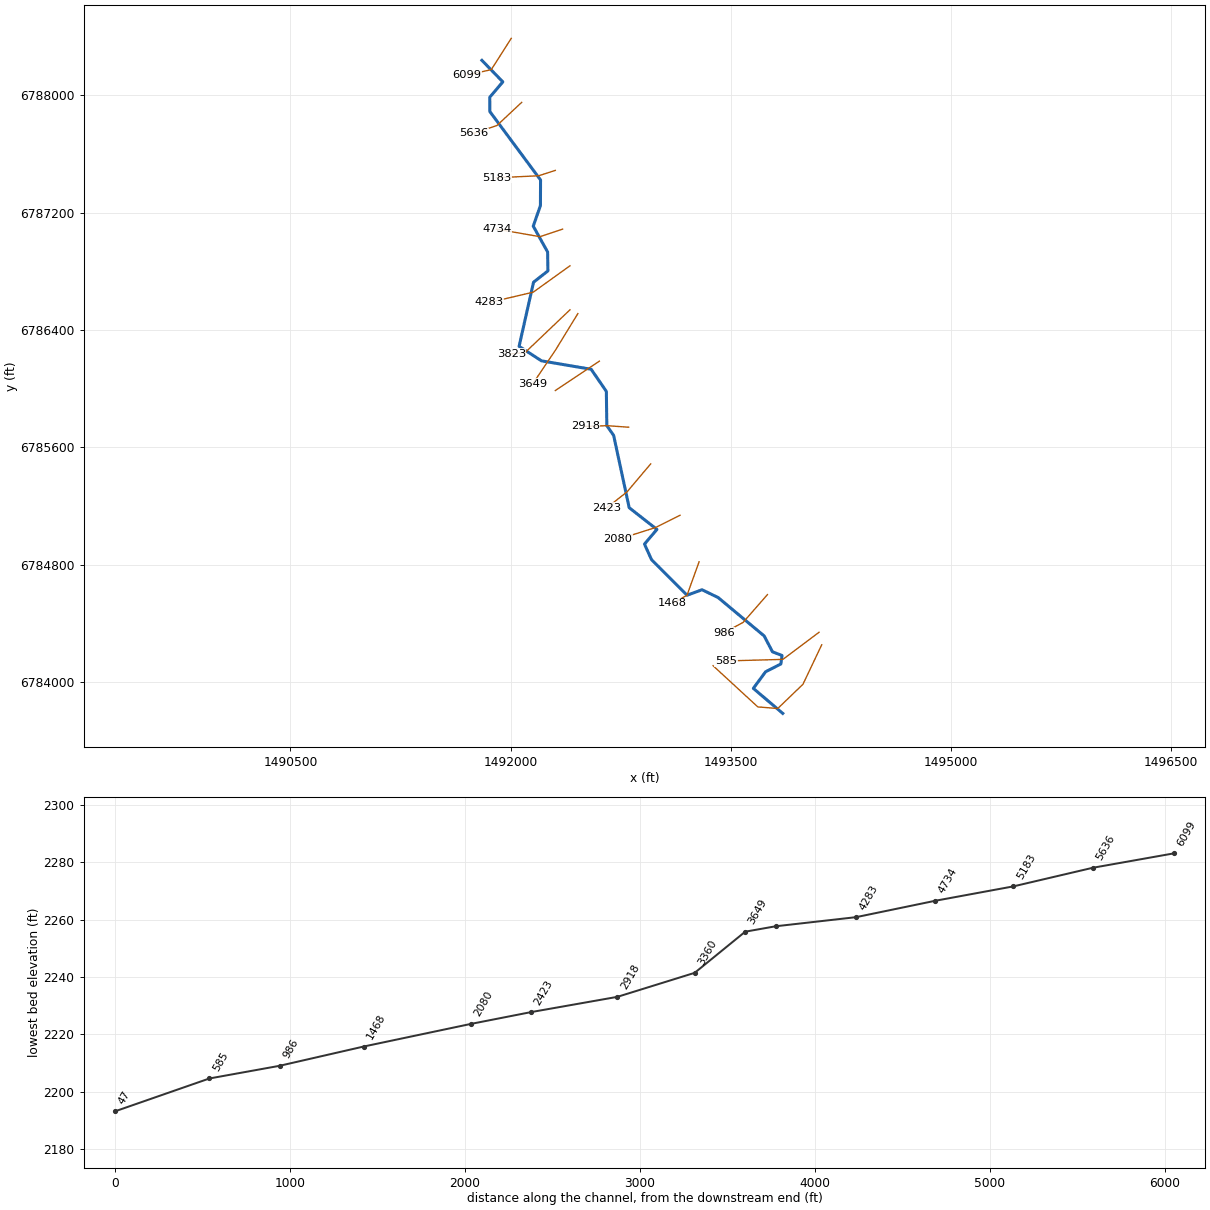
--- Elm 21.prj (project) ---

Proj Title=Elm 21 Base Level Engineering
Current Plan=p01
Default Exp/Contr=0.3,0.1
English Units
Geom File=g01
Flow File=f01
Plan File=p01
BEGIN DESCRIPTION:
Elm 21
END DESCRIPTION:

--- Elm 21.p01 (plan) ---

Plan Title=Multiple Run
Short Identifier=Multiple
Geom File=g01
Flow File=f01
Subcritical Flow
K Sum by GR= 0
Std Step Tol= 0.01
Critical Tol= 0.01
Num of Std Step Trials= 20
Max Error Tol= 0.3
Flow Tol Ratio= 0.001
Split Flow NTrial= 30
Split Flow Tol= 0.02
Split Flow Ratio= 0.02
Log Output Level= 0
Friction Slope Method= 1
Unsteady Friction Slope Method= 2
Unsteady Bridges Friction Slope Method= 1
Parabolic Critical Depth
Global Vel Dist=  1 , 1 , 1
Global Log Level= 0
CheckData=True
Encroach Param= -1, 0, 0, 0
BEGIN DESCRIPTION:
Multiple Run
END DESCRIPTION:

--- Elm 21.f01 (steady flow) ---

Flow Title=Multiple
Number of Profiles=7
Profile Names=10-year,25-year,50-year,1pct_min,100-year,1pct_plu,500-year
River Rch & RM= Elm 21,Reach-1,6099
     336     479     601     468     750    1030    1180
River Rch & RM= Elm 21,Reach-1,3360
     402     579     730     571     914    1260    1450
Boundary for River Rch & Prof#=Elm 21,Reach-1,1
Up Type=0
Dn Type=3
Dn Slope=0.005
Boundary for River Rch & Prof#=Elm 21,Reach-1,2
Up Type=0
Dn Type=3
Dn Slope=0.005
Boundary for River Rch & Prof#=Elm 21,Reach-1,3
Up Type=0
Dn Type=3
Dn Slope=0.005
Boundary for River Rch & Prof#=Elm 21,Reach-1,4
Up Type=0
Dn Type=3
Dn Slope=0.005
Boundary for River Rch & Prof#=Elm 21,Reach-1,5
Up Type=0
Dn Type=3
Dn Slope=0.005
Boundary for River Rch & Prof#=Elm 21,Reach-1,6
Up Type=0
Dn Type=3
Dn Slope=0.005
Boundary for River Rch & Prof#=Elm 21,Reach-1,7
Up Type=0
Dn Type=3
Dn Slope=0.005

--- Elm 21.g01 (geometry) ---

Geom Title=Existing Conditions

River Reach=Elm 21,Reach-1
Reach XY= 30
      1491805.00      6788238.00      1491947.41      6788091.34
      1491858.48      6787986.50      1491858.67      6787889.59
      1492204.62      6787422.84      1492203.78      6787248.50
      1492154.89      6787108.09      1492252.77      6786932.07
      1492254.67      6786803.05      1492156.76      6786726.12
      1492058.37      6786289.28      1492210.93      6786190.25
      1492549.56      6786132.81      1492652.94      6785982.15
      1492656.22      6785748.50      1492702.73      6785682.06
      1492808.61      6785189.48      1492997.50      6785041.58
      1492912.80      6784941.41      1492960.80      6784835.71
      1493202.71      6784593.11      1493305.00      6784630.44
      1493414.68      6784577.25      1493728.83      6784315.13
      1493784.74      6784207.70      1493850.24      6784182.34
      1493842.13      6784124.67      1493737.99      6784071.42
      1493654.57      6783958.35      1493855.00      6783788.00

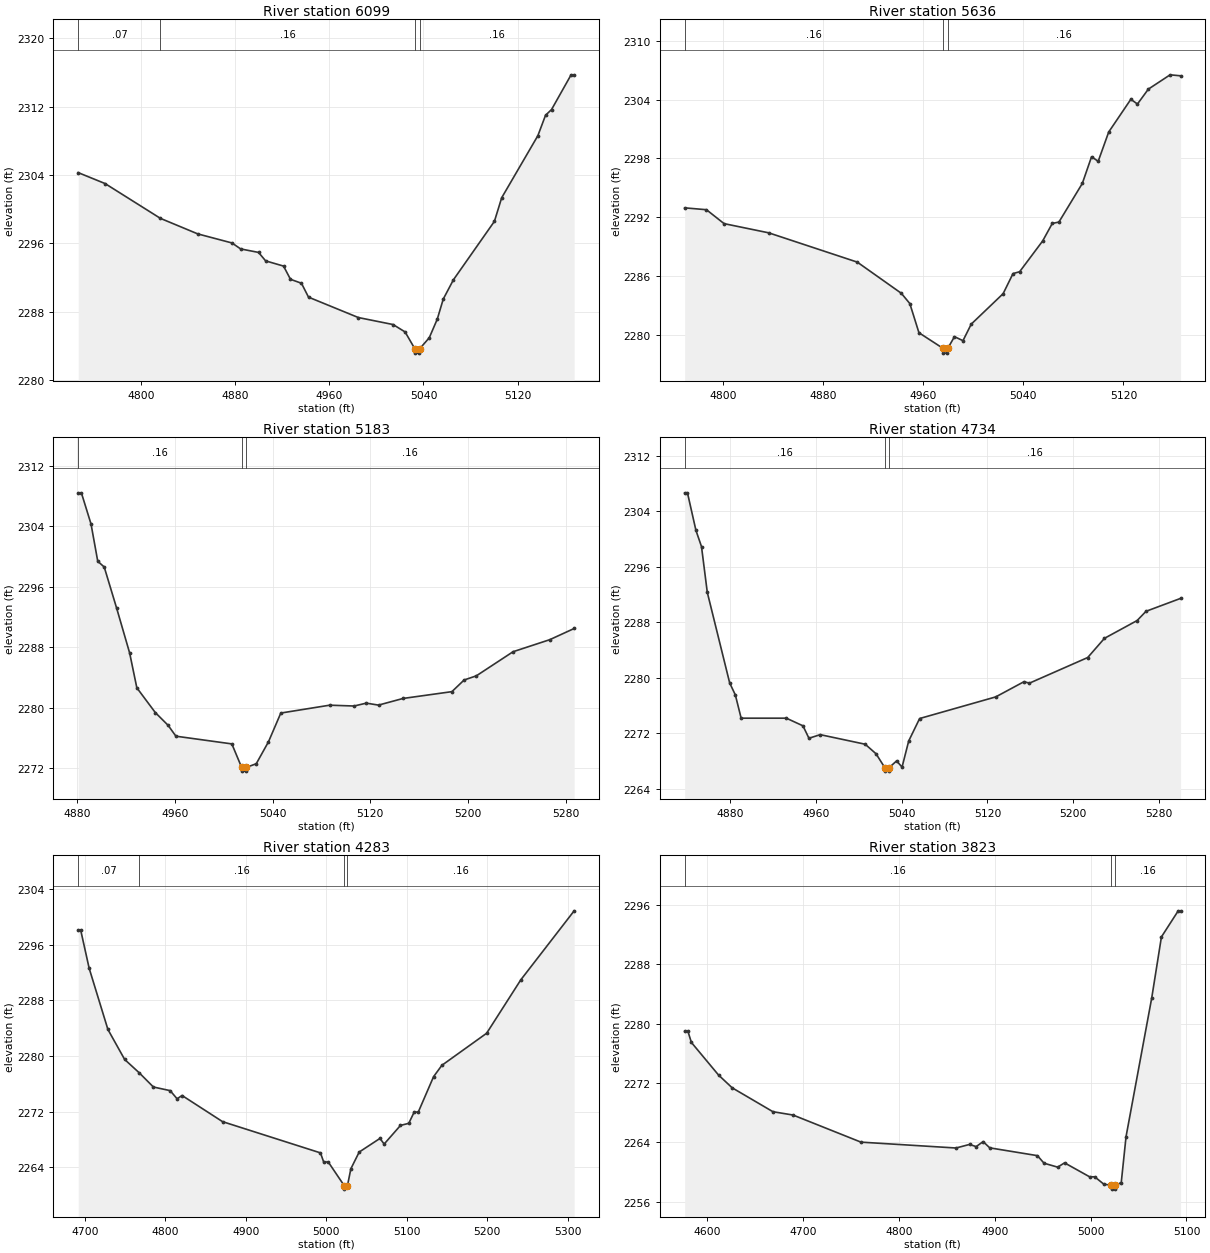
Type RM Length L Ch R = 1,6099,463,463,463
BEGIN DESCRIPTION:
360
END DESCRIPTION:
XS GIS Cut Line= 3
      1492005.00      6788388.00      1491868.82      6788174.67
      1491704.97      6788137.99
#Sta/Elev= 30
  4746.9 2304.28  4769.7 2303.00  4816.7 2298.92  4848.4 2297.10  4877.4 2296.04
  4884.8 2295.34  4900.0 2294.93  4906.0 2293.94  4921.2 2293.33  4927.1 2291.78
  4936.4 2291.32  4942.4 2289.69  4984.7 2287.30  5014.2 2286.48  5024.4 2285.61
  5032.7 2283.63  5032.9 2283.13  5036.4 2283.13  5036.7 2283.63  5044.9 2284.93
  5051.7 2287.11  5056.8 2289.47  5065.4 2291.72  5100.2 2298.57  5106.4 2301.34
  5137.1 2308.61  5143.6 2311.00  5148.7 2311.67  5165.3 2315.74  5167.9 2315.74
#Mann=4,-1,0
  4746.9    0.07       0  4816.7    0.16       0  5032.7    0.07       0
  5036.7    0.16       0
Bank Sta=5032.7,5036.7
Exp/Cntr=0.3,0.1

Type RM Length L Ch R = 1,5636,453,453,453
BEGIN DESCRIPTION:
359
END DESCRIPTION:
XS GIS Cut Line= 3
      1492076.05      6787951.69      1491907.49      6787794.03
      1491750.57      6787740.82
#Sta/Elev= 30
  4769.2 2292.94  4786.6 2292.75  4800.7 2291.33  4836.4 2290.39  4907.2 2287.40
  4942.4 2284.22  4949.2 2283.17  4956.5 2280.19  4975.6 2278.61  4975.8 2278.11
  4979.3 2278.11  4979.6 2278.61  4984.9 2279.79  4991.7 2279.38  4998.3 2281.07
  5023.8 2284.18  5031.7 2286.23  5037.0 2286.42  5055.4 2289.56  5063.1 2291.35
  5068.4 2291.49  5087.1 2295.43  5094.5 2298.16  5099.8 2297.69  5108.2 2300.68
  5125.9 2304.02  5131.2 2303.54  5139.9 2305.06  5157.3 2306.52  5165.7 2306.42
#Mann=3,-1,0
  4769.2    0.16       0  4975.6    0.07       0  4979.6    0.16       0
Bank Sta=4975.6,4979.6
Exp/Cntr=0.3,0.1

Type RM Length L Ch R = 1,5183,449,449,449
BEGIN DESCRIPTION:
358
END DESCRIPTION:
XS GIS Cut Line= 3
      1492305.01      6787488.00      1492191.60      6787451.31
      1491905.01      6787438.00
#Sta/Elev= 30
  4880.8 2308.43  4883.4 2308.43  4891.3 2304.30  4896.8 2299.38  4902.1 2298.62
  4912.3 2293.16  4922.9 2287.26  4928.8 2282.65  4943.9 2279.38  4954.4 2277.69
  4960.8 2276.25  5006.6 2275.23  5014.6 2272.13  5014.9 2271.63  5018.4 2271.63
  5018.6 2272.13  5026.6 2272.61  5036.6 2275.51  5046.7 2279.31  5086.7 2280.35
  5106.7 2280.24  5116.7 2280.62  5126.7 2280.36  5146.8 2281.24  5186.8 2282.14
  5196.8 2283.68  5206.8 2284.23  5236.9 2287.42  5266.9 2289.01  5286.9 2290.49
#Mann=3,-1,0
  4880.8    0.16       0  5014.6    0.07       0  5018.6    0.16       0
Bank Sta=5014.6,5018.6
Exp/Cntr=0.3,0.1

Type RM Length L Ch R = 1,4734,451,451,451
BEGIN DESCRIPTION:
357
END DESCRIPTION:
XS GIS Cut Line= 3
      1492354.96      6787087.99      1492200.81      6787036.27
      1491905.00      6787088.00
#Sta/Elev= 30
  4837.4 2306.63  4840.0 2306.63  4847.9 2301.23  4853.1 2298.89  4858.5 2292.31
  4879.4 2279.27  4884.7 2277.54  4890.1 2274.20  4932.3 2274.20  4947.8 2273.10
  4953.4 2271.31  4963.9 2271.83  5005.9 2270.45  5016.0 2269.08  5024.2 2267.08
  5024.4 2266.58  5027.9 2266.58  5028.2 2267.08  5035.2 2268.05  5040.3 2267.16
  5046.5 2270.92  5056.7 2274.15  5127.7 2277.26  5154.1 2279.45  5159.2 2279.24
  5213.6 2282.93  5229.2 2285.69  5259.7 2288.25  5268.0 2289.58  5300.3 2291.44
#Mann=3,-1,0
  4837.4    0.16       0  5024.2    0.07       0  5028.2    0.16       0
Bank Sta=5024.2,5028.2
Exp/Cntr=0.3,0.1

Type RM Length L Ch R = 1,4283,460,460,460
BEGIN DESCRIPTION:
356
END DESCRIPTION:
XS GIS Cut Line= 3
      1492405.03      6786838.02      1492154.69      6786658.26
      1491855.01      6786588.00
#Sta/Elev= 30
  4691.8 2298.11  4694.9 2298.11  4705.4 2292.63  4728.7 2283.83  4749.5 2279.52
  4767.7 2277.59  4785.2 2275.56  4806.0 2275.04  4814.6 2273.87  4820.8 2274.34
  4871.1 2270.58  4992.7 2266.09  4996.7 2264.78  5002.4 2264.78  5022.2 2261.38
  5022.4 2260.88  5026.2 2261.38  5030.5 2263.82  5040.8 2266.21  5066.6 2268.17
  5071.8 2267.36  5092.1 2270.04  5102.4 2270.34  5109.1 2271.96  5114.2 2271.96
  5133.2 2277.05  5143.5 2278.68  5199.1 2283.29  5241.6 2290.98  5307.8 2300.89
#Mann=4,-1,0
  4691.8    0.07       0  4767.7    0.16       0  5022.2    0.07       0
  5026.2    0.16       0
Bank Sta=5022.2,5026.2
Exp/Cntr=0.3,0.1

Type RM Length L Ch R = 1,3823,174,174,174
BEGIN DESCRIPTION:
355
END DESCRIPTION:
XS GIS Cut Line= 3
      1492404.97      6786537.97      1492098.61      6786246.00
      1492005.05      6786238.00
#Sta/Elev= 30
  4576.8 2278.95  4580.2 2278.95  4583.8 2277.46  4612.1 2273.07  4626.3 2271.35
  4668.8 2268.13  4689.8 2267.68  4760.6 2264.03  4859.7 2263.24  4873.8 2263.72
  4880.7 2263.43  4888.0 2264.10  4894.9 2263.26  4944.6 2262.21  4951.5 2261.19
  4965.7 2260.66  4972.9 2261.24  4999.0 2259.36  5004.3 2259.36  5013.7 2258.38
  5021.7 2258.20  5021.9 2257.70  5025.4 2257.70  5025.7 2258.20  5032.0 2258.59
  5037.0 2264.77  5063.8 2283.47  5073.9 2291.68  5091.4 2295.19  5093.9 2295.19
#Mann=3,-1,0
  4576.8    0.16       0  5021.7    0.07       0  5025.7    0.16       0
Bank Sta=5021.7,5025.7
Exp/Cntr=0.3,0.1

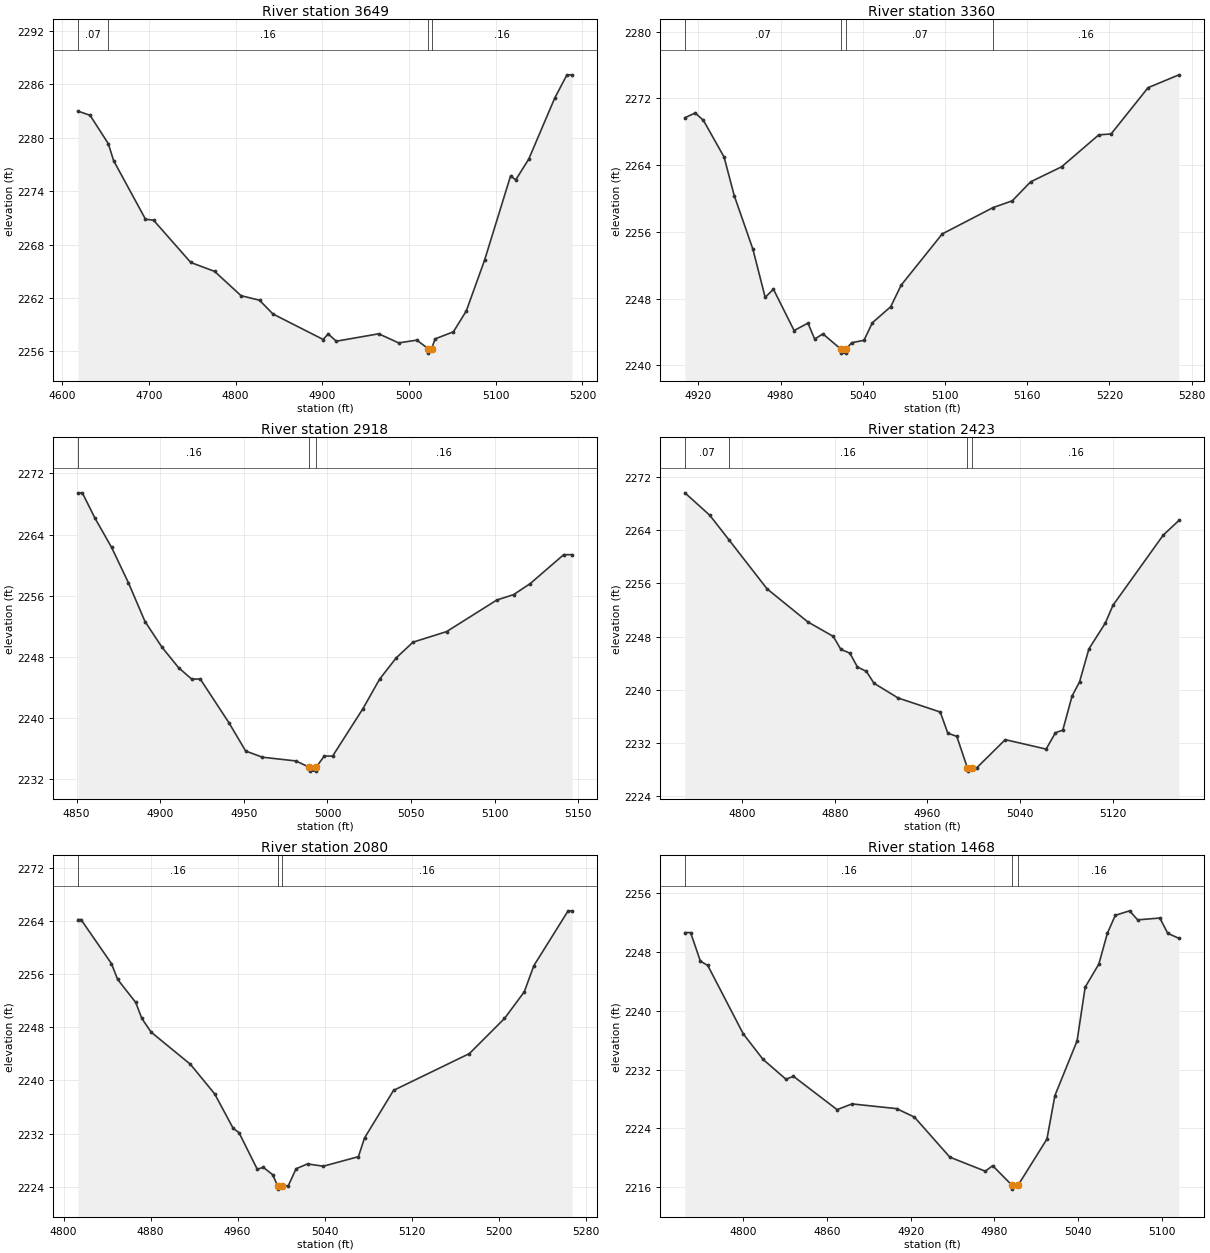
Type RM Length L Ch R = 1,3649,289,289,289
BEGIN DESCRIPTION:
841
END DESCRIPTION:
XS GIS Cut Line= 3
      1492458.82      6786512.31      1492306.27      6786263.41
      1492151.02      6786033.20
#Sta/Elev= 30
  4618.4 2282.98  4632.3 2282.52  4653.4 2279.32  4659.5 2277.42  4696.2 2270.85
  4705.6 2270.73  4748.4 2265.99  4775.9 2264.99  4806.4 2262.26  4827.7 2261.75
  4843.1 2260.21  4901.1 2257.34  4906.8 2257.97  4916.2 2257.15  4965.1 2257.98
  4988.1 2256.96  5009.1 2257.27  5022.1 2256.31  5022.4 2255.81  5026.1 2256.31
  5030.1 2257.41  5051.2 2258.20  5066.1 2260.55  5087.1 2266.23  5117.1 2275.70
  5123.1 2275.27  5138.1 2277.60  5168.0 2284.44  5182.1 2287.06  5188.0 2287.06
#Mann=4,-1,0
  4618.4    0.07       0  4653.4    0.16       0  5022.1    0.07       0
  5026.1    0.16       0
Bank Sta=5022.1,5026.1
Exp/Cntr=0.3,0.1

Type RM Length L Ch R = 1,3360,442,442,442
BEGIN DESCRIPTION:
354
END DESCRIPTION:
XS GIS Cut Line= 3
      1492605.00      6786188.00      1492530.20      6786138.31
      1492305.04      6785988.03
#Sta/Elev= 30
  4910.2 2269.69  4917.7 2270.25  4923.7 2269.38  4938.8 2264.97  4946.2 2260.35
  4959.8 2253.93  4968.8 2248.14  4974.8 2249.12  4989.9 2244.16  5000.0 2245.05
  5004.9 2243.14  5010.9 2243.76  5023.9 2241.95  5024.2 2241.45  5027.7 2241.45
  5027.9 2241.95  5031.9 2242.70  5040.9 2242.99  5047.0 2245.09  5060.4 2247.02
  5068.0 2249.60  5098.0 2255.75  5135.1 2258.91  5149.1 2259.72  5162.5 2262.00
  5185.1 2263.80  5212.2 2267.63  5221.2 2267.74  5248.2 2273.29  5270.7 2274.83
#Mann=4,-1,0
  4910.2    0.07       0  5023.9    0.07       0  5027.9    0.07       0
  5135.1    0.16       0
Bank Sta=5023.9,5027.9
Exp/Cntr=0.3,0.1

Type RM Length L Ch R = 1,2918,495,495,495
BEGIN DESCRIPTION:
353
END DESCRIPTION:
XS GIS Cut Line= 3
      1492805.05      6785738.00      1492656.22      6785748.50
      1492510.00      6785743.61
#Sta/Elev= 30
  4850.8 2269.47  4853.4 2269.47  4860.9 2266.18  4870.9 2262.33  4880.9 2257.74
  4890.9 2252.63  4901.0 2249.29  4911.0 2246.59  4918.9 2245.09  4923.9 2245.13
  4941.1 2239.39  4951.1 2235.70  4961.1 2234.89  4981.2 2234.40  4989.2 2233.57
  4989.4 2233.07  4992.9 2233.07  4993.2 2233.57  4998.1 2235.04  5003.1 2235.04
  5021.2 2241.23  5031.2 2245.10  5041.2 2247.90  5051.2 2249.94  5071.3 2251.32
  5101.3 2255.45  5111.3 2256.15  5121.3 2257.60  5141.3 2261.38  5146.3 2261.38
#Mann=3,-1,0
  4850.8    0.16       0  4989.2    0.07       0  4993.2    0.16       0
Bank Sta=4989.2,4993.2
Exp/Cntr=0.3,0.1

Type RM Length L Ch R = 1,2423,343,343,343
BEGIN DESCRIPTION:
352
END DESCRIPTION:
XS GIS Cut Line= 3
      1492955.03      6785488.03      1492794.10      6785297.63
      1492655.01      6785188.01
#Sta/Elev= 30
  4750.7 2269.65  4772.2 2266.27  4789.1 2262.49  4821.6 2255.19  4856.7 2250.22
  4878.8 2248.02  4885.3 2246.07  4893.1 2245.50  4899.6 2243.42  4907.4 2242.75
  4913.9 2240.97  4934.7 2238.75  4971.1 2236.63  4977.6 2233.46  4985.4 2232.96
  4994.5 2228.23  4994.7 2227.73  4998.5 2228.23  5002.6 2228.23  5027.2 2232.47
  5062.5 2231.05  5070.5 2233.51  5076.9 2233.92  5084.9 2239.06  5091.3 2241.16
  5099.4 2246.14  5113.5 2250.01  5120.2 2252.72  5163.5 2263.27  5177.1 2265.49
#Mann=4,-1,0
  4750.7    0.07       0  4789.1    0.16       0  4994.5    0.07       0
  4998.5    0.16       0
Bank Sta=4994.5,4998.5
Exp/Cntr=0.3,0.1

Type RM Length L Ch R = 1,2080,612,612,612
BEGIN DESCRIPTION:
351
END DESCRIPTION:
XS GIS Cut Line= 3
      1493155.04      6785138.02      1492988.31      6785054.45
      1492733.15      6784973.47
#Sta/Elev= 30
  4813.3 2264.23  4816.1 2264.23  4844.1 2257.59  4849.7 2255.23  4866.4 2251.74
  4872.0 2249.34  4880.5 2247.28  4916.7 2242.42  4939.0 2237.96  4955.8 2232.83
  4961.4 2232.11  4978.1 2226.62  4983.7 2226.90  4992.3 2225.79  4996.8 2224.12
  4997.1 2223.62  5000.9 2224.12  5006.6 2224.13  5013.8 2226.69  5024.3 2227.42
  5038.8 2227.07  5071.1 2228.51  5076.7 2231.32  5103.4 2238.50  5173.1 2244.04
  5205.4 2249.33  5223.6 2253.35  5232.4 2257.29  5263.9 2265.55  5267.5 2265.55
#Mann=3,-1,0
  4813.3    0.16       0  4996.8    0.07       0  5000.9    0.16       0
Bank Sta=4996.8,5000.9
Exp/Cntr=0.3,0.1

Type RM Length L Ch R = 1,1468,482,482,482
BEGIN DESCRIPTION:
350
END DESCRIPTION:
XS GIS Cut Line= 3
      1493284.76      6784820.67      1493202.71      6784593.11
      1493104.99      6784537.99
#Sta/Elev= 30
  4758.1 2250.63  4762.2 2250.63  4769.2 2246.75  4774.5 2246.16  4799.9 2236.87
  4814.1 2233.39  4830.6 2230.68  4835.9 2231.09  4867.2 2226.55  4877.9 2227.33
  4909.8 2226.69  4922.6 2225.54  4948.0 2220.09  4973.4 2218.18  4978.7 2218.93
  4992.7 2216.24  4992.9 2215.74  4996.8 2216.24  5017.6 2222.55  5023.3 2228.46
  5039.2 2235.90  5045.0 2243.21  5054.8 2246.35  5060.9 2250.53  5066.6 2252.98
  5076.8 2253.59  5082.6 2252.36  5098.5 2252.61  5104.2 2250.53  5112.2 2249.85
#Mann=3,-1,0
  4758.1    0.16       0  4992.7    0.07       0  4996.8    0.16       0
Bank Sta=4992.7,4996.8
Exp/Cntr=0.3,0.1

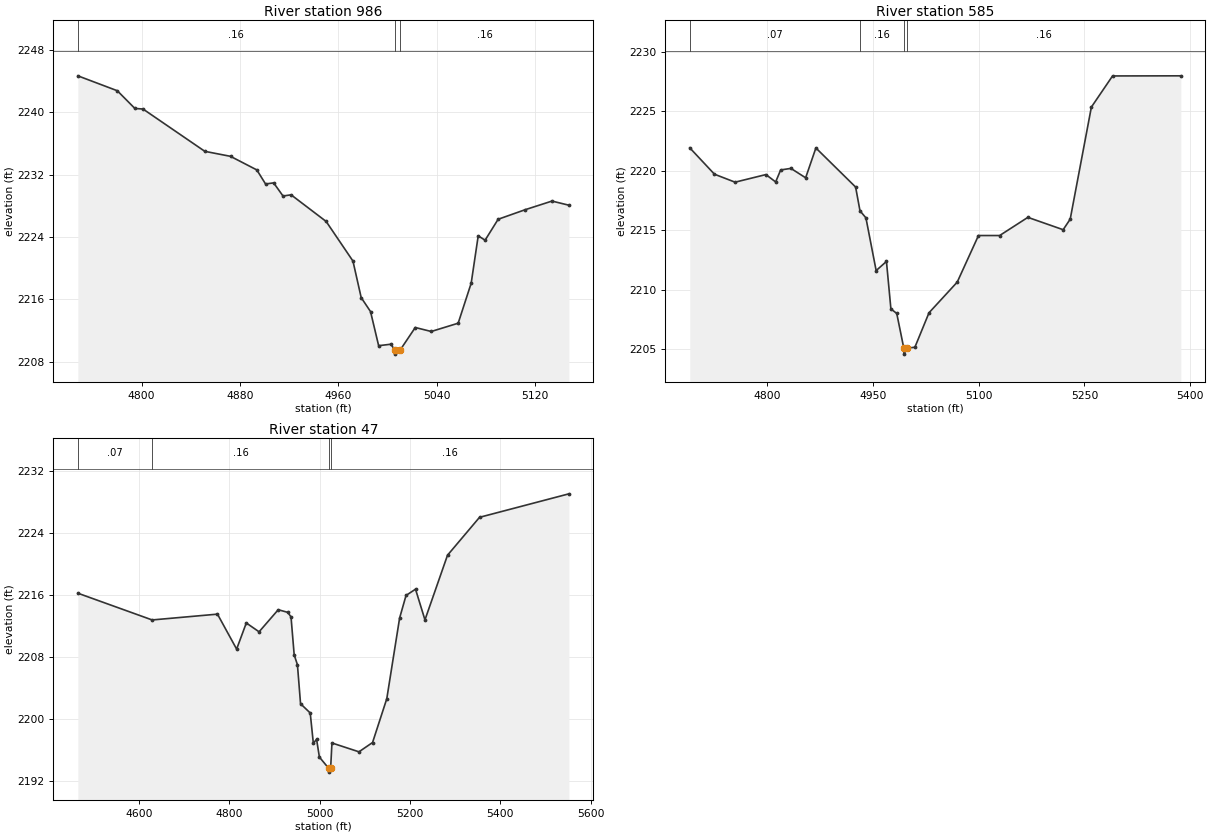
Type RM Length L Ch R = 1,986,401,401,401
BEGIN DESCRIPTION:
349
END DESCRIPTION:
XS GIS Cut Line= 3
      1493750.82      6784597.55      1493585.02      6784408.04
      1493454.99      6784337.99
#Sta/Elev= 30
  4748.2 2244.64  4780.3 2242.73  4794.6 2240.46  4801.2 2240.39  4851.5 2234.97
  4872.4 2234.33  4893.8 2232.59  4900.9 2230.79  4907.5 2230.93  4915.1 2229.25
  4921.7 2229.40  4950.2 2225.99  4972.0 2220.92  4978.7 2216.24  4986.3 2214.45
  4992.9 2210.08  5002.9 2210.27  5006.1 2209.50  5006.4 2209.00  5010.3 2209.50
  5022.7 2212.41  5035.7 2211.90  5057.6 2212.96  5068.2 2218.09  5073.9 2224.15
  5079.5 2223.59  5090.1 2226.27  5112.0 2227.49  5133.9 2228.60  5147.7 2228.07
#Mann=3,-1,0
  4748.2    0.16       0  5006.1    0.07       0  5010.3    0.16       0
Bank Sta=5006.1,5010.3
Exp/Cntr=0.3,0.1

Type RM Length L Ch R = 1,585,538,538,538
BEGIN DESCRIPTION:
767
END DESCRIPTION:
XS GIS Cut Line= 3
      1494102.28      6784340.84      1493856.26      6784155.94
      1493468.27      6784145.29
#Sta/Elev= 30
  4690.7 2221.94  4725.7 2219.72  4754.9 2219.05  4798.6 2219.69  4812.4 2219.07
  4819.5 2220.08  4834.0 2220.21  4854.9 2219.42  4869.4 2221.93  4925.7 2218.64
  4931.9 2216.64  4940.3 2216.05  4954.8 2211.61  4969.4 2212.38  4975.7 2208.39
  4984.0 2208.00  4994.0 2205.08  4994.3 2204.58  4998.2 2205.08  5009.7 2205.16
  5029.7 2208.06  5069.7 2210.64  5099.8 2214.56  5129.8 2214.56  5169.8 2216.09
  5219.8 2215.05  5229.8 2215.94  5259.8 2225.37  5289.8 2227.99  5386.6 2228.00
#Mann=4,-1,0
  4690.7    0.07       0  4931.9    0.16       0  4994.0    0.07       0
  4998.2    0.16       0
Bank Sta=4994,4998.2
Exp/Cntr=0.3,0.1

Type RM Length L Ch R = 1,47,0,0,0
BEGIN DESCRIPTION:
348
END DESCRIPTION:
XS GIS Cut Line= 5
      1494120.62      6784255.28      1493992.85      6783986.44
      1493821.11      6783821.29      1493685.11      6783831.98
      1493380.04      6784112.97
#Sta/Elev= 30
  4464.8 2216.23  4629.3 2212.78  4773.9 2213.53  4816.3 2209.02  4837.7 2212.39
  4866.0 2211.25  4908.4 2214.10  4929.5 2213.76  4936.7 2213.17  4943.7 2208.28
  4950.9 2207.00  4957.8 2201.97  4979.2 2200.78  4986.1 2196.88  4993.3 2197.38
  4999.5 2195.09  5020.0 2193.65  5020.3 2193.15  5024.4 2193.65  5027.3 2196.91
  5087.1 2195.77  5117.2 2196.97  5148.7 2202.62  5177.1 2213.03  5191.3 2215.94
  5212.3 2216.75  5233.2 2212.79  5283.1 2221.13  5354.0 2226.02  5551.9 2229.05
#Mann=4,-1,0
  4464.8    0.07       0  4629.3    0.16       0  5020.0    0.07       0
  5024.4    0.16       0
Bank Sta=5020,5024.4
Exp/Cntr=0.3,0.1

Chan Stop Cuts=-1