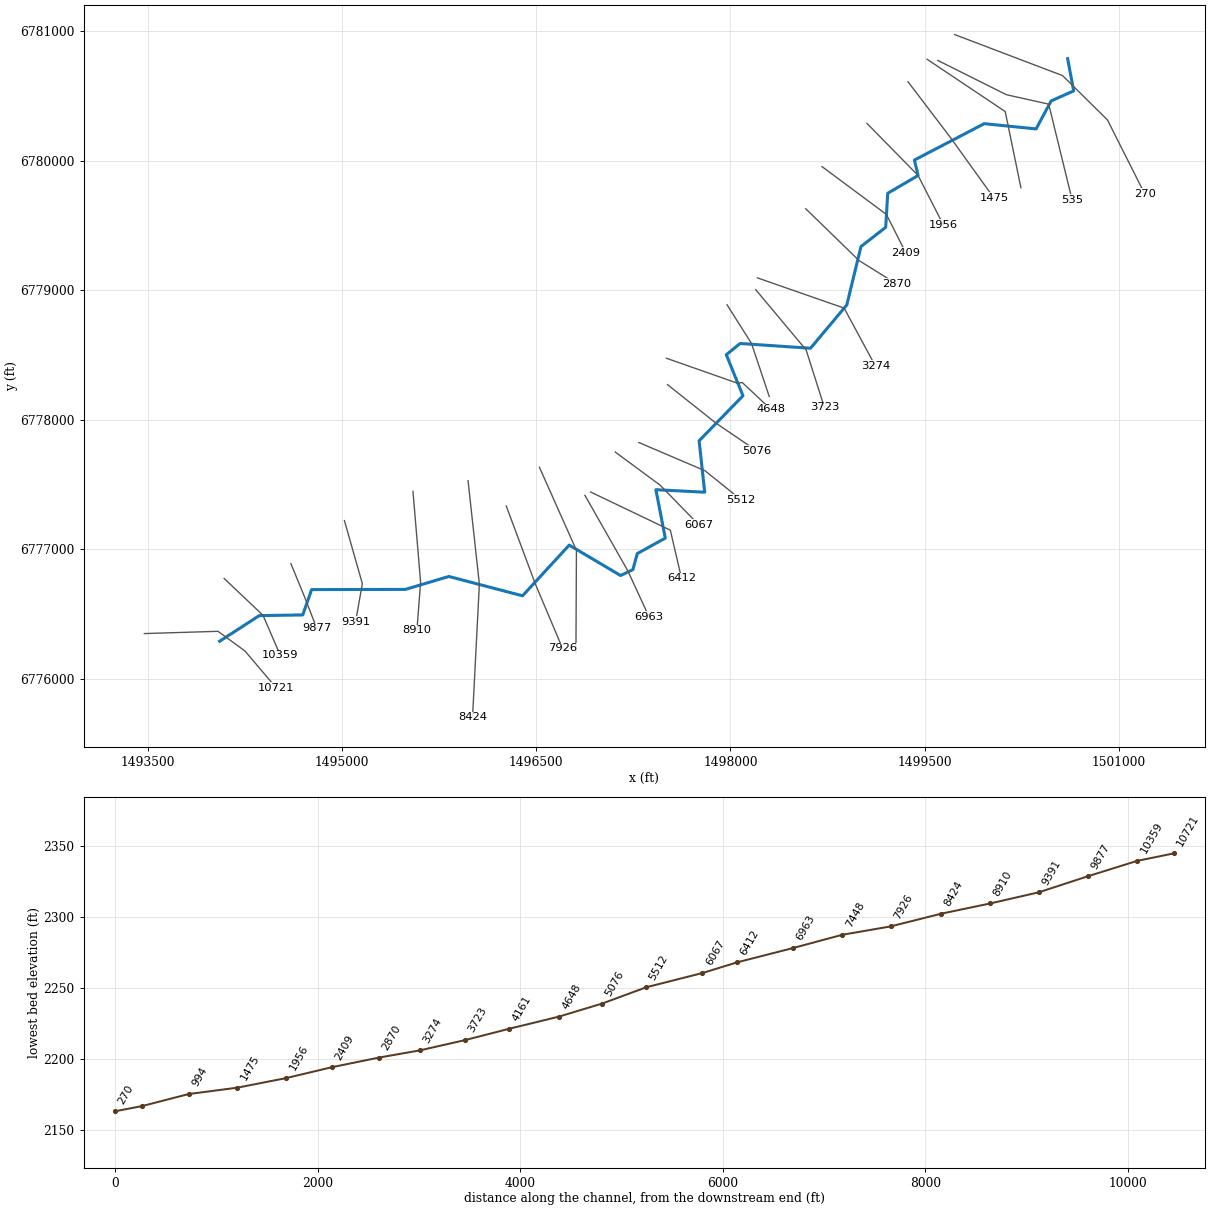
--- Elm 22.prj (project) ---

Proj Title=Elm 22 Base Level Engineering
Current Plan=p01
Default Exp/Contr=0.3,0.1
English Units
Geom File=g01
Flow File=f01
Plan File=p01
BEGIN DESCRIPTION:
Elm 22
END DESCRIPTION:

--- Elm 22.p01 (plan) ---

Plan Title=Multiple Run
Short Identifier=Multiple
Geom File=g01
Flow File=f01
Subcritical Flow
K Sum by GR= 0
Std Step Tol= 0.01
Critical Tol= 0.01
Num of Std Step Trials= 20
Max Error Tol= 0.3
Flow Tol Ratio= 0.001
Split Flow NTrial= 30
Split Flow Tol= 0.02
Split Flow Ratio= 0.02
Log Output Level= 0
Friction Slope Method= 1
Unsteady Friction Slope Method= 2
Unsteady Bridges Friction Slope Method= 1
Parabolic Critical Depth
Global Vel Dist=  1 , 1 , 1
Global Log Level= 0
CheckData=True
Encroach Param= -1, 0, 0, 0
BEGIN DESCRIPTION:
Multiple Run
END DESCRIPTION:

--- Elm 22.f01 (steady flow) ---

Flow Title=Multiple
Number of Profiles=7
Profile Names=10-year,25-year,50-year,1pct_min,100-year,1pct_plu,500-year
River Rch & RM= Elm 22,Reach-1,10721
     345     493     619     483     774    1060    1220
River Rch & RM= Elm 22,Reach-1,3274
     451     655     832     654    1050    1440    1690
Boundary for River Rch & Prof#=Elm 22,Reach-1,1
Up Type=0
Dn Type=3
Dn Slope=0.005
Boundary for River Rch & Prof#=Elm 22,Reach-1,2
Up Type=0
Dn Type=3
Dn Slope=0.005
Boundary for River Rch & Prof#=Elm 22,Reach-1,3
Up Type=0
Dn Type=3
Dn Slope=0.005
Boundary for River Rch & Prof#=Elm 22,Reach-1,4
Up Type=0
Dn Type=3
Dn Slope=0.005
Boundary for River Rch & Prof#=Elm 22,Reach-1,5
Up Type=0
Dn Type=3
Dn Slope=0.005
Boundary for River Rch & Prof#=Elm 22,Reach-1,6
Up Type=0
Dn Type=3
Dn Slope=0.005
Boundary for River Rch & Prof#=Elm 22,Reach-1,7
Up Type=0
Dn Type=3
Dn Slope=0.005

--- Elm 22.g01 (geometry) ---

Geom Title=Existing Conditions

River Reach=Elm 22,Reach-1
Reach XY= 30
      1494055.00      6776288.00      1494360.86      6776485.94
      1494696.89      6776491.31      1494765.26      6776687.02
      1495489.79      6776688.51      1495825.15      6776788.36
      1496394.57      6776639.03      1496754.90      6777030.68
      1497151.62      6776795.76      1497246.83      6776841.34
      1497281.00      6776965.31      1497497.21      6777084.57
      1497424.38      6777458.66      1497801.55      6777439.19
      1497758.46      6777836.50      1498097.33      6778184.34
      1497968.32      6778501.33      1498074.98      6778588.04
      1498618.67      6778551.22      1498899.17      6778885.70
      1499008.61      6779336.52      1499199.64      6779485.30
      1499215.32      6779748.17      1499449.89      6779885.70
      1499421.30      6780004.70      1499960.86      6780285.93
      1500361.34      6780245.36      1500477.81      6780461.95
      1500651.64      6780539.25      1500605.00      6780788.00

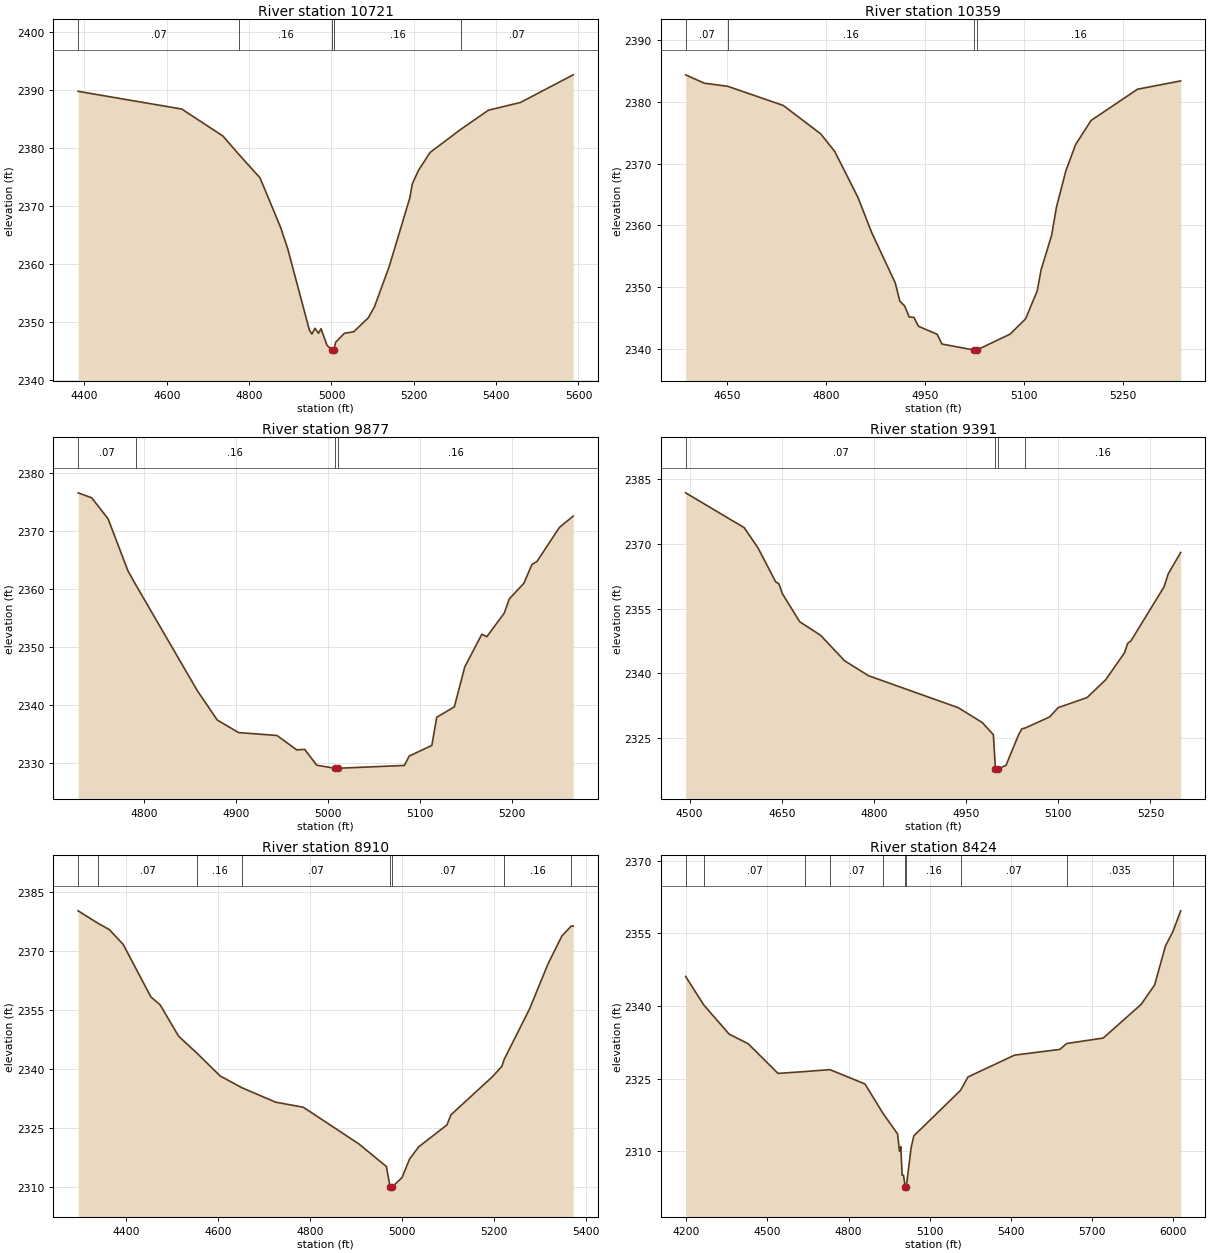
Type RM Length L Ch R = 1,10721,362,362,362
BEGIN DESCRIPTION:
elmc294
END DESCRIPTION:
XS GIS Cut Line= 4
      1493473.55      6776347.38      1494042.16      6776364.74
      1494250.49      6776212.84      1494493.55      6775926.37
#Sta/Elev= 30
  4384.8 2389.71  4636.4 2386.66  4736.4 2382.02  4774.6 2378.90  4826.5 2374.82
  4876.5 2366.29  4894.0 2362.57  4946.5 2348.59  4952.6 2347.94  4960.0 2348.93
  4968.5 2348.07  4974.7 2348.85  4989.4 2345.98  5002.0 2345.15  5002.3 2344.65
  5006.0 2345.15  5010.2 2346.52  5031.4 2348.06  5054.2 2348.33  5089.8 2350.75
  5104.5 2352.63  5140.0 2359.50  5190.2 2371.32  5196.4 2373.78  5211.1 2376.07
  5239.6 2379.19  5314.8 2383.20  5381.3 2386.46  5459.3 2387.80  5587.2 2392.55
#Mann=5,-1,0
  4384.8    0.07       0  4774.6    0.16       0  5002.0    0.07       0
  5006.0    0.16       0  5314.8    0.07       0
Bank Sta=5002,5006
Exp/Cntr=0.3,0.1

Type RM Length L Ch R = 1,10359,482,482,482
BEGIN DESCRIPTION:
elmc167
END DESCRIPTION:
XS GIS Cut Line= 3
      1494089.90      6776772.74      1494389.80      6776488.49
      1494523.92      6776178.13
#Sta/Elev= 30
  4586.8 2384.36  4615.0 2383.01  4650.9 2382.50  4735.1 2379.40  4791.8 2374.82
  4813.2 2371.95  4848.4 2364.52  4869.4 2358.80  4905.0 2350.70  4911.9 2347.77
  4919.2 2346.98  4926.1 2345.22  4933.3 2345.13  4940.2 2343.70  4968.5 2342.41
  4975.8 2340.83  5024.7 2339.86  5025.0 2339.36  5028.7 2339.86  5079.2 2342.43
  5102.7 2344.90  5120.4 2349.42  5126.2 2352.81  5142.2 2358.39  5149.7 2363.02
  5163.9 2368.84  5178.6 2373.07  5202.1 2376.98  5272.6 2382.03  5338.1 2383.38
#Mann=4,-1,0
  4586.8    0.07       0  4650.9    0.16       0  5024.7    0.07       0
  5028.7    0.16       0
Bank Sta=5024.7,5028.7
Exp/Cntr=0.3,0.1

Type RM Length L Ch R = 1,9877,486,486,486
BEGIN DESCRIPTION:
elmc166
END DESCRIPTION:
XS GIS Cut Line= 3
      1494605.00      6776888.01      1494708.45      6776636.77
      1494805.02      6776387.95
#Sta/Elev= 30
  4728.3 2376.64  4743.0 2375.78  4760.8 2372.18  4782.4 2363.21  4791.1 2360.74
  4858.1 2342.47  4879.7 2337.44  4902.9 2335.28  4944.6 2334.78  4966.2 2332.29
  4974.7 2332.39  4987.9 2329.65  5007.5 2329.13  5007.8 2328.63  5011.5 2329.13
  5083.2 2329.61  5088.5 2331.23  5113.1 2333.06  5118.4 2337.92  5137.6 2339.72
  5148.9 2346.60  5167.5 2352.25  5172.9 2351.82  5191.8 2355.87  5197.4 2358.34
  5213.2 2361.03  5222.0 2364.28  5227.4 2364.78  5251.9 2370.67  5266.9 2372.63
#Mann=4,-1,0
  4728.3    0.07       0  4791.1    0.16       0  5007.5    0.07       0
  5011.5    0.16       0
Bank Sta=5007.5,5011.5
Exp/Cntr=0.3,0.1

Type RM Length L Ch R = 1,9391,481,481,481
BEGIN DESCRIPTION:
elmc165
END DESCRIPTION:
XS GIS Cut Line= 3
      1495018.74      6777219.73      1495157.18      6776732.62
      1495105.00      6776438.01
#Sta/Elev= 30
  4493.6 2381.87  4589.0 2373.78  4611.5 2369.07  4640.1 2361.23  4645.3 2360.78
  4651.3 2358.41  4679.2 2351.97  4713.1 2348.83  4752.2 2342.92  4791.3 2339.43
  4937.2 2332.02  4976.3 2328.58  4994.4 2325.75  4997.8 2317.80  4998.1 2317.30
  5001.8 2317.80  5014.9 2318.63  5035.2 2325.66  5040.7 2327.12  5046.1 2327.30
  5085.9 2329.87  5099.8 2332.03  5146.9 2334.37  5177.3 2338.52  5207.8 2344.76
  5213.0 2346.96  5218.1 2347.47  5272.2 2360.07  5278.9 2363.06  5299.2 2368.03
#Mann=4,-1,0
  4493.6    0.07       0  4997.8    0.07       0  5001.8    0.07       0
  5046.1    0.16       0
Bank Sta=4997.8,5001.8
Exp/Cntr=0.3,0.1

Type RM Length L Ch R = 1,8910,486,486,486
BEGIN DESCRIPTION:
elmc164
END DESCRIPTION:
XS GIS Cut Line= 3
      1495548.24      6777445.44      1495607.18      6776744.12
      1495578.62      6776373.42
#Sta/Elev= 30
  4296.2 2380.14  4339.8 2376.94  4363.9 2375.37  4394.0 2371.61  4454.2 2358.27
  4474.3 2356.25  4514.4 2348.29  4554.1 2343.99  4604.7 2338.18  4652.1 2335.18
  4725.2 2331.52  4785.4 2330.23  4905.8 2320.94  4966.0 2315.16  4974.0 2309.92
  4974.3 2309.42  4978.0 2309.92  5000.0 2312.37  5016.2 2317.05  5036.2 2320.18
  5097.4 2325.73  5106.4 2328.33  5196.7 2338.03  5216.8 2340.62  5222.0 2342.42
  5276.9 2355.20  5317.1 2366.65  5347.1 2373.72  5367.4 2376.27  5371.8 2376.27
#Mann=8,-1,0
  4296.2    0.16       0  4339.8    0.07       0  4554.1    0.16       0
  4652.1    0.07       0  4974.0    0.07       0  4978.0    0.07       0
  5222.0    0.16       0  5367.4    0.07       0
Bank Sta=4974,4978
Exp/Cntr=0.3,0.1

Type RM Length L Ch R = 1,8424,498,498,498
BEGIN DESCRIPTION:
elmc163
END DESCRIPTION:
XS GIS Cut Line= 3
      1495973.58      6777527.98      1496061.06      6776729.86
      1496008.36      6775701.81
#Sta/Elev= 30
  4197.1 2346.12  4264.1 2340.24  4358.0 2334.21  4428.5 2332.22  4539.1 2326.08
  4639.3 2326.47  4731.3 2326.86  4861.0 2323.90  4927.7 2317.82  4981.7 2313.57
  4988.5 2310.01  4993.6 2310.95  4998.4 2305.05  5003.4 2305.05  5009.9 2302.67
  5010.1 2302.17  5013.9 2302.67  5031.9 2310.81  5041.9 2313.19  5214.6 2322.58
  5242.2 2325.35  5414.4 2329.86  5582.6 2331.05  5607.0 2332.26  5742.8 2333.39
  5883.0 2340.34  5933.1 2344.37  5973.1 2352.42  6000.2 2355.34  6029.4 2359.68
#Mann=10,-1,0
  4197.1    0.16       0  4264.1    0.07       0  4639.3    0.16       0
  4731.3    0.07       0  4927.7    0.16       0  5009.9    0.07       0
  5013.9    0.16       0  5214.6    0.07       0  5607.0   0.035       0
  6000.2    0.16       0
Bank Sta=5009.9,5013.9
Exp/Cntr=0.3,0.1

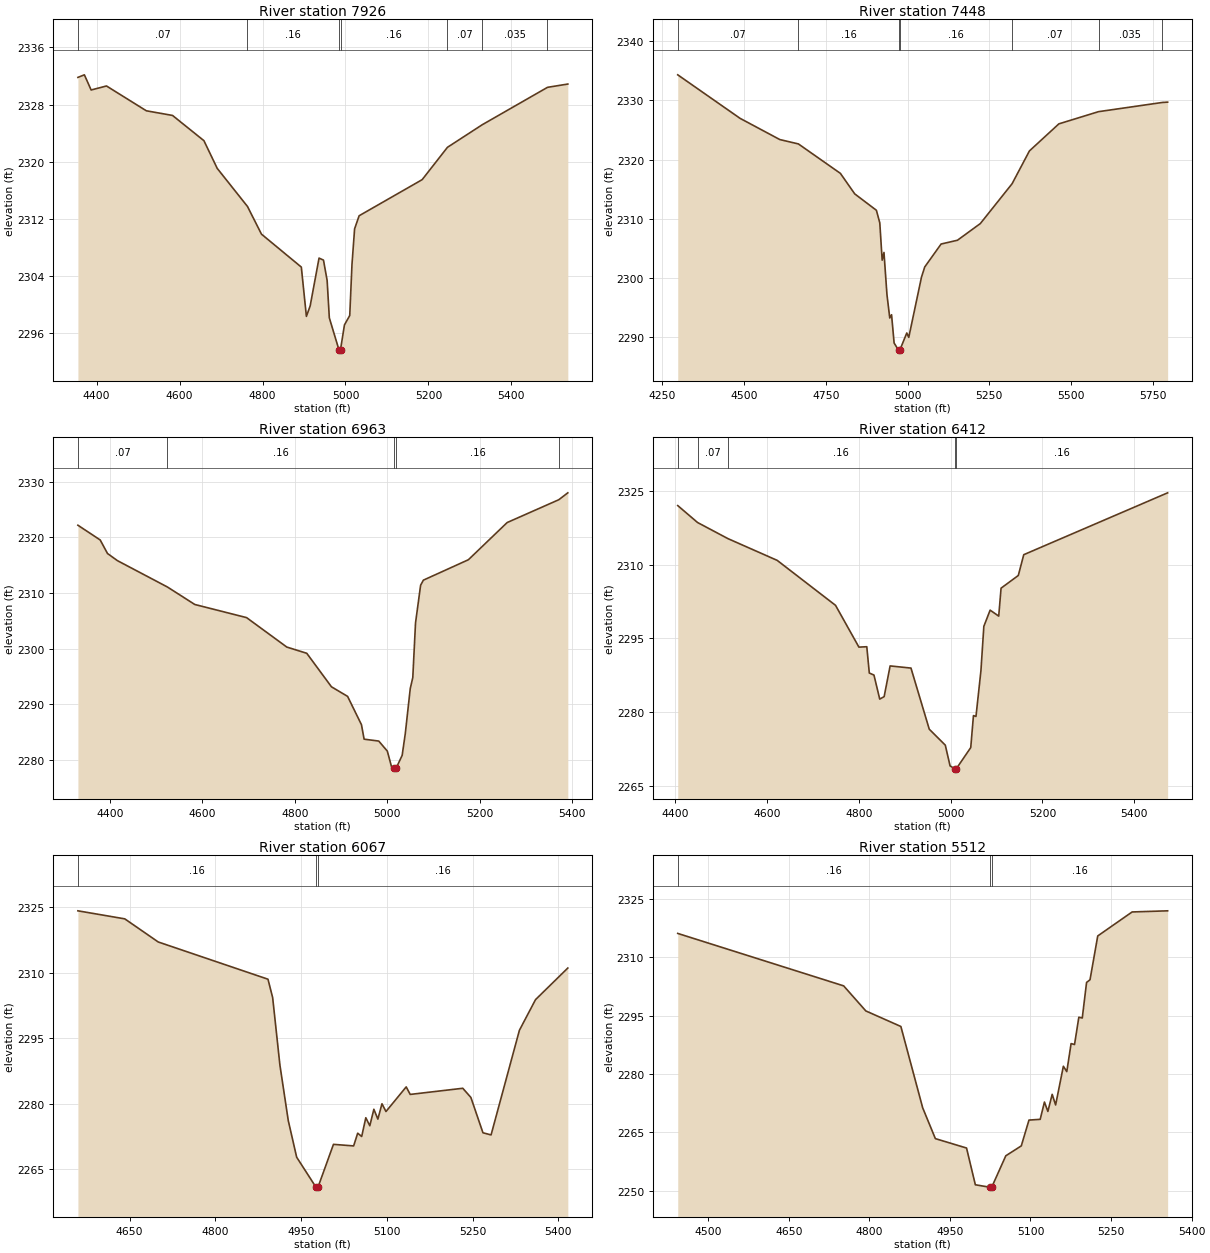
Type RM Length L Ch R = 1,7926,478,478,478
BEGIN DESCRIPTION:
elmc162
END DESCRIPTION:
XS GIS Cut Line= 3
      1496268.73      6777332.60      1496494.23      6776728.30
      1496702.76      6776234.53
#Sta/Elev= 30
  4355.0 2331.80  4370.6 2332.16  4386.9 2330.04  4423.9 2330.60  4520.0 2327.13
  4583.1 2326.48  4658.8 2322.95  4690.8 2319.08  4763.8 2313.75  4797.5 2309.88
  4893.6 2305.27  4905.8 2298.38  4914.9 2299.84  4936.3 2306.53  4947.0 2306.25
  4955.8 2303.40  4961.1 2298.17  4984.1 2293.74  4984.4 2293.24  4988.1 2293.74
  4997.5 2297.18  5010.3 2298.50  5015.7 2305.65  5022.0 2310.62  5032.9 2312.45
  5184.9 2317.50  5245.8 2322.02  5329.4 2325.17  5487.0 2330.41  5536.0 2330.87
#Mann=7,-1,0
  4355.0    0.07       0  4763.8    0.16       0  4984.1    0.07       0
  4988.1    0.16       0  5245.8    0.07       0  5329.4   0.035       0
  5487.0    0.07       0
Bank Sta=4984.1,4988.1
Exp/Cntr=0.3,0.1

Type RM Length L Ch R = 1,7448,485,485,485
BEGIN DESCRIPTION:
elmc161
END DESCRIPTION:
XS GIS Cut Line= 3
      1496524.80      6777632.10      1496810.86      6776990.48
      1496806.92      6776195.49
#Sta/Elev= 30
  4297.5 2334.33  4488.1 2326.98  4609.5 2323.40  4666.4 2322.66  4794.7 2317.69
  4838.5 2314.23  4904.7 2311.46  4915.1 2309.34  4922.4 2303.04  4927.9 2304.34
  4937.0 2297.23  4945.6 2293.27  4951.1 2293.82  4958.9 2289.05  4972.3 2287.84
  4972.6 2287.34  4976.3 2287.84  4997.6 2290.74  5003.7 2290.00  5042.5 2300.16
  5052.5 2301.89  5102.5 2305.76  5152.5 2306.40  5222.5 2309.22  5319.5 2315.94
  5372.5 2321.48  5462.5 2326.05  5583.7 2328.11  5778.4 2329.66  5795.0 2329.72
#Mann=7,-1,0
  4297.5    0.07       0  4666.4    0.16       0  4972.3    0.07       0
  4976.3    0.16       0  5319.5    0.07       0  5583.7   0.035       0
  5778.4    0.07       0
Bank Sta=4972.3,4976.3
Exp/Cntr=0.3,0.1

Type RM Length L Ch R = 1,6963,551,551,551
BEGIN DESCRIPTION:
elmc160
END DESCRIPTION:
XS GIS Cut Line= 3
      1496876.35      6777415.12      1497207.08      6776833.36
      1497370.58      6776478.84
#Sta/Elev= 30
  4330.8 2322.20  4379.0 2319.55  4394.8 2317.12  4416.4 2315.83  4524.4 2311.10
  4583.6 2307.96  4695.6 2305.60  4782.6 2300.31  4825.8 2299.19  4879.2 2293.17
  4914.1 2291.45  4944.1 2286.36  4949.8 2283.76  4981.5 2283.42  5000.0 2281.62
  5009.2 2278.78  5014.9 2278.52  5015.2 2278.02  5018.9 2278.52  5032.1 2280.85
  5038.9 2284.79  5049.6 2292.84  5055.1 2294.83  5061.0 2304.63  5072.0 2311.41
  5078.0 2312.33  5175.4 2316.00  5259.2 2322.68  5370.9 2326.78  5390.4 2328.02
#Mann=5,-1,0
  4330.8    0.07       0  4524.4    0.16       0  5014.9    0.07       0
  5018.9    0.16       0  5370.9   0.035       0
Bank Sta=5014.9,5018.9
Exp/Cntr=0.3,0.1

Type RM Length L Ch R = 1,6412,345,345,345
BEGIN DESCRIPTION:
elmc159
END DESCRIPTION:
XS GIS Cut Line= 3
      1496919.76      6777441.14      1497536.09      6777145.99
      1497622.85      6776772.90
#Sta/Elev= 30
  4406.1 2322.06  4449.3 2318.61  4515.4 2315.33  4622.6 2310.90  4749.6 2301.74
  4800.5 2293.23  4817.6 2293.31  4823.1 2287.95  4833.2 2287.54  4845.8 2282.64
  4855.4 2283.15  4868.4 2289.40  4913.8 2288.96  4953.6 2276.51  4988.5 2273.26
  4998.9 2269.04  5008.6 2268.47  5008.9 2267.97  5012.6 2268.47  5043.9 2272.77
  5049.8 2279.28  5055.3 2279.11  5066.1 2288.45  5072.4 2297.46  5086.1 2300.76
  5104.8 2299.55  5109.9 2305.24  5147.4 2307.82  5159.3 2312.06  5472.5 2324.66
#Mann=5,-1,0
  4406.1    0.16       0  4449.3    0.07       0  4515.4    0.16       0
  5008.6    0.07       0  5012.6    0.16       0
Bank Sta=5008.6,5012.6
Exp/Cntr=0.3,0.1

Type RM Length L Ch R = 1,6067,555,555,555
BEGIN DESCRIPTION:
elmc158
END DESCRIPTION:
XS GIS Cut Line= 3
      1497110.74      6777749.29      1497457.96      6777493.22
      1497754.97      6777188.03
#Sta/Elev= 30
  4559.5 2324.18  4641.5 2322.34  4700.1 2317.04  4892.1 2308.51  4900.3 2304.29
  4913.0 2288.83  4927.6 2276.13  4942.3 2267.73  4975.8 2260.91  4976.0 2260.41
  4979.8 2260.91  5006.7 2270.67  5042.0 2270.31  5049.1 2273.23  5056.1 2272.47
  5063.3 2276.77  5070.3 2274.93  5077.4 2278.71  5084.4 2276.45  5091.6 2279.97
  5098.6 2278.19  5134.0 2283.84  5141.0 2282.11  5233.0 2283.52  5247.2 2281.41
  5268.3 2273.32  5282.5 2272.83  5332.1 2296.81  5360.3 2303.83  5416.8 2311.07
#Mann=3,-1,0
  4559.5    0.16       0  4975.8    0.07       0  4979.8    0.16       0
Bank Sta=4975.8,4979.8
Exp/Cntr=0.3,0.1

Type RM Length L Ch R = 1,5512,436,436,436
BEGIN DESCRIPTION:
elmc157
END DESCRIPTION:
XS GIS Cut Line= 3
      1497293.05      6777823.07      1497804.80      6777604.44
      1498081.50      6777381.55
#Sta/Elev= 30
  4443.5 2316.13  4752.3 2302.64  4793.6 2296.19  4858.8 2292.19  4899.4 2271.27
  4923.0 2263.35  4981.0 2260.93  4997.4 2251.48  5023.9 2250.86  5024.2 2250.36
  5027.9 2250.86  5054.1 2258.94  5082.9 2261.48  5097.2 2268.12  5118.1 2268.31
  5126.0 2272.76  5132.4 2270.34  5140.4 2274.74  5146.8 2272.01  5161.2 2281.96
  5167.6 2280.59  5175.6 2287.79  5182.0 2287.55  5190.0 2294.56  5196.4 2294.38
  5204.4 2303.52  5210.8 2304.20  5225.2 2315.48  5289.2 2321.65  5355.3 2321.94
#Mann=3,-1,0
  4443.5    0.16       0  5023.9    0.07       0  5027.9    0.16       0
Bank Sta=5023.9,5027.9
Exp/Cntr=0.3,0.1

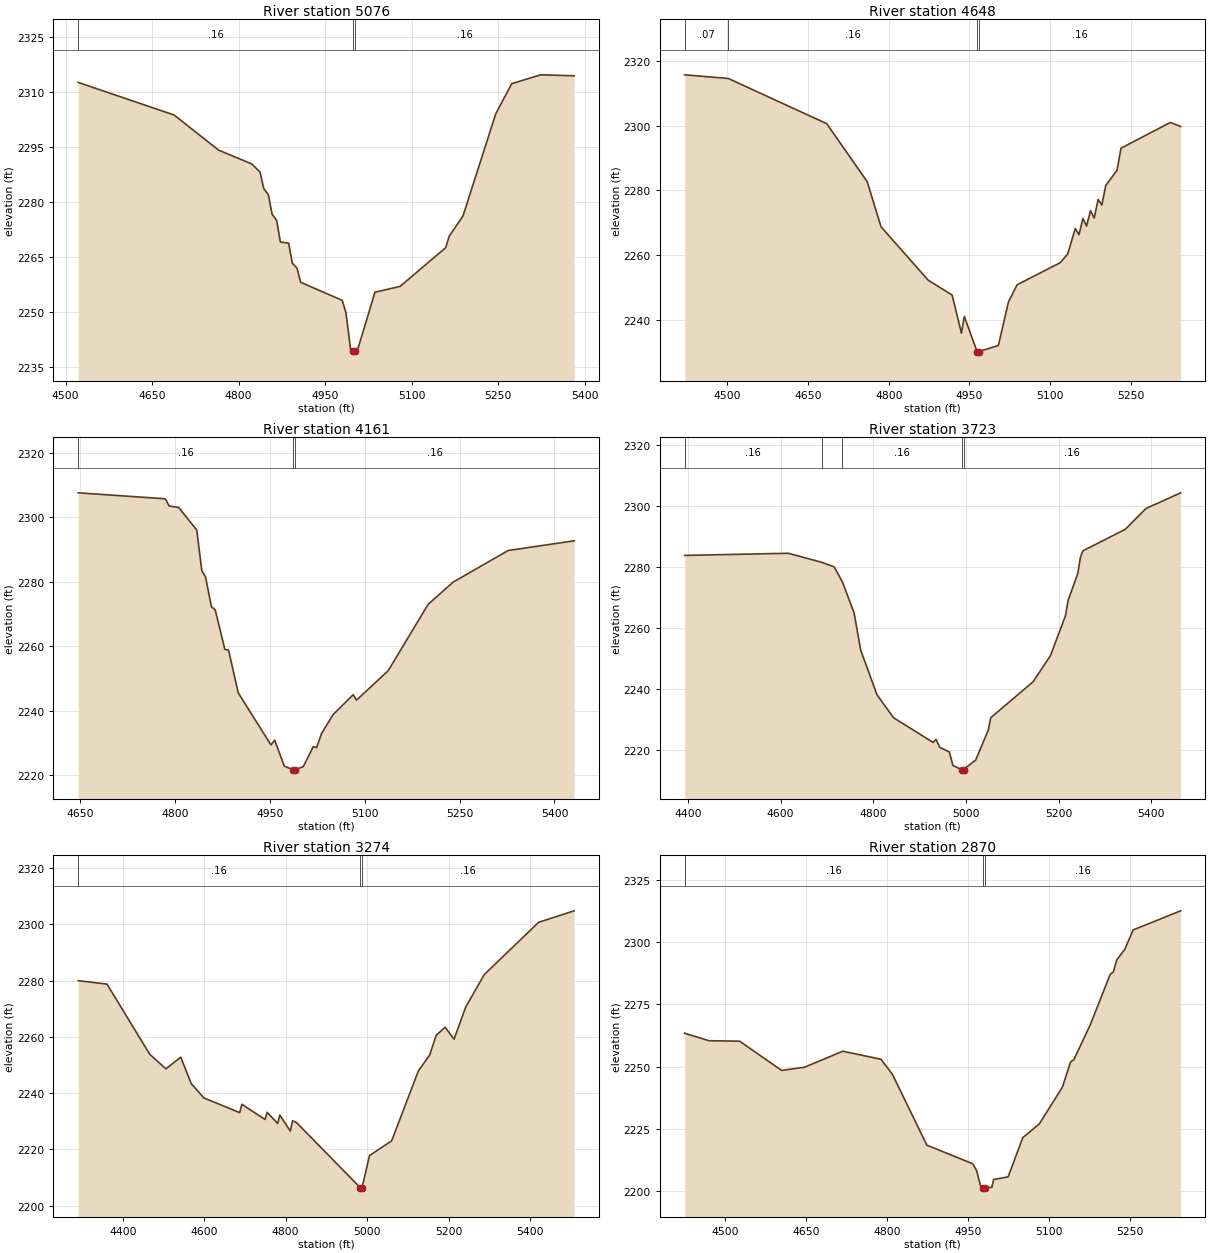
Type RM Length L Ch R = 1,5076,428,428,428
BEGIN DESCRIPTION:
elmc156
END DESCRIPTION:
XS GIS Cut Line= 3
      1497514.40      6778270.11      1497888.76      6777972.73
      1498204.45      6777758.00
#Sta/Elev= 30
  4521.9 2312.53  4688.2 2303.66  4765.3 2294.11  4822.8 2290.36  4837.2 2288.13
  4843.6 2283.66  4851.6 2281.95  4858.0 2276.72  4866.0 2274.96  4872.4 2269.11
  4886.8 2268.80  4893.2 2263.36  4901.3 2262.01  4907.6 2258.15  4979.8 2253.24
  4986.2 2249.83  4994.2 2239.92  4997.8 2239.39  4998.0 2238.89  5001.8 2239.39
  5007.6 2240.45  5036.4 2255.46  5080.1 2257.05  5159.1 2267.58  5165.2 2270.72
  5189.0 2276.18  5245.9 2304.00  5273.6 2312.19  5323.8 2314.59  5381.8 2314.33
#Mann=3,-1,0
  4521.9    0.16       0  4997.8    0.07       0  5001.8    0.16       0
Bank Sta=4997.8,5001.8
Exp/Cntr=0.3,0.1

Type RM Length L Ch R = 1,4648,487,487,487
BEGIN DESCRIPTION:
elmc155
END DESCRIPTION:
XS GIS Cut Line= 4
      1497505.72      6778474.11      1498052.54      6778281.94
      1498091.76      6778286.47      1498313.01      6778079.14
#Sta/Elev= 30
  4420.4 2315.74  4501.6 2314.61  4684.6 2300.63  4759.8 2282.71  4785.5 2268.76
  4873.1 2252.25  4917.8 2247.63  4935.1 2235.84  4940.4 2241.02  4964.1 2230.17
  4964.3 2229.67  4968.1 2230.17  5003.8 2232.04  5022.6 2245.54  5038.6 2250.81
  5118.5 2257.61  5132.7 2260.33  5146.8 2268.21  5153.7 2266.30  5161.0 2271.33
  5167.8 2268.97  5175.1 2273.71  5182.0 2271.44  5189.3 2277.21  5196.2 2275.45
  5203.5 2281.51  5224.5 2286.24  5231.8 2293.04  5323.6 2301.01  5342.7 2299.76
#Mann=4,-1,0
  4420.4    0.07       0  4501.6    0.16       0  4964.1    0.07       0
  4968.1    0.16       0
Bank Sta=4964.1,4968.1
Exp/Cntr=0.3,0.1

Type RM Length L Ch R = 1,4161,438,438,438
BEGIN DESCRIPTION:
elmc154
END DESCRIPTION:
XS GIS Cut Line= 3
      1497974.44      6778886.47      1498163.25      6778587.86
      1498299.96      6778179.01
#Sta/Elev= 30
  4646.7 2307.55  4784.5 2305.70  4790.4 2303.48  4805.7 2303.01  4834.2 2296.00
  4842.2 2283.42  4848.1 2281.46  4857.4 2272.22  4863.4 2271.24  4878.6 2259.01
  4884.5 2258.75  4899.8 2245.50  4951.5 2229.34  4957.5 2230.80  4972.7 2222.73
  4986.0 2221.70  4986.2 2221.20  4990.0 2221.70  5002.6 2222.58  5018.5 2228.78
  5023.8 2228.49  5031.5 2232.86  5050.1 2238.80  5081.6 2244.91  5086.9 2243.24
  5136.9 2252.33  5200.2 2272.96  5239.6 2279.83  5326.7 2289.65  5431.1 2292.66
#Mann=3,-1,0
  4646.7    0.16       0  4986.0    0.07       0  4990.0    0.16       0
Bank Sta=4986,4990
Exp/Cntr=0.3,0.1

Type RM Length L Ch R = 1,3723,449,449,449
BEGIN DESCRIPTION:
elmc153
END DESCRIPTION:
XS GIS Cut Line= 3
      1498195.81      6779003.63      1498585.12      6778537.91
      1498725.31      6778096.54
#Sta/Elev= 30
  4393.0 2283.92  4616.6 2284.62  4689.2 2281.64  4715.5 2280.16  4733.1 2275.31
  4758.5 2265.10  4772.8 2252.85  4807.9 2238.25  4843.5 2230.73  4928.9 2222.60
  4935.4 2223.59  4943.2 2220.99  4964.1 2219.47  4971.9 2215.02  4990.7 2213.68
  4990.9 2213.18  4994.7 2213.68  5021.1 2216.85  5048.1 2226.62  5053.4 2230.70
  5144.9 2242.49  5182.4 2251.09  5214.7 2264.16  5220.2 2269.09  5241.2 2277.98
  5246.9 2283.30  5252.2 2285.41  5343.7 2292.47  5388.1 2299.28  5463.1 2304.44
#Mann=5,-1,0
  4393.0    0.16       0  4689.2    0.07       0  4733.1    0.16       0
  4990.7    0.07       0  4994.7    0.16       0
Bank Sta=4990.7,4994.7
Exp/Cntr=0.3,0.1

Type RM Length L Ch R = 1,3274,404,404,404
BEGIN DESCRIPTION:
elmc152
END DESCRIPTION:
XS GIS Cut Line= 3
      1498208.87      6779094.77      1498878.71      6778861.18
      1499120.13      6778413.64
#Sta/Elev= 30
  4290.6 2280.02  4361.3 2278.80  4466.5 2253.81  4506.1 2248.68  4542.4 2252.82
  4568.2 2243.41  4599.3 2238.33  4687.2 2233.11  4692.5 2236.07  4749.4 2230.68
  4754.6 2233.23  4780.4 2229.24  4785.7 2232.24  4811.5 2226.55  4816.8 2230.19
  4826.6 2229.59  4983.5 2206.41  4983.7 2205.91  4987.5 2206.41  5006.0 2217.85
  5060.3 2223.08  5126.0 2247.94  5153.6 2253.56  5169.8 2260.64  5191.7 2263.46
  5213.6 2259.23  5242.2 2270.64  5287.7 2282.19  5421.2 2300.76  5508.5 2304.85
#Mann=3,-1,0
  4290.6    0.16       0  4983.5    0.07       0  4987.5    0.16       0
Bank Sta=4983.5,4987.5
Exp/Cntr=0.3,0.1

Type RM Length L Ch R = 1,2870,461,461,461
BEGIN DESCRIPTION:
elmc151
END DESCRIPTION:
XS GIS Cut Line= 3
      1498582.11      6779628.62      1498994.10      6779228.37
      1499285.24      6779047.02
#Sta/Elev= 30
  4425.6 2263.40  4470.6 2260.39  4527.2 2260.21  4604.9 2248.47  4647.3 2249.76
  4718.1 2256.18  4788.8 2252.95  4809.9 2246.89  4873.7 2218.47  4958.6 2211.00
  4965.5 2208.32  4972.7 2202.38  4977.5 2201.33  4977.8 2200.83  4981.9 2201.33
  4993.8 2201.56  4997.1 2204.70  5023.9 2205.74  5051.0 2221.49  5081.7 2227.03
  5124.2 2241.71  5139.5 2251.92  5145.4 2252.73  5176.1 2266.89  5212.7 2287.03
  5218.6 2288.03  5224.9 2292.82  5239.8 2297.08  5255.2 2304.87  5343.0 2312.53
#Mann=3,-1,0
  4425.6    0.16       0  4977.5    0.07       0  4981.9    0.16       0
Bank Sta=4977.5,4981.9
Exp/Cntr=0.3,0.1

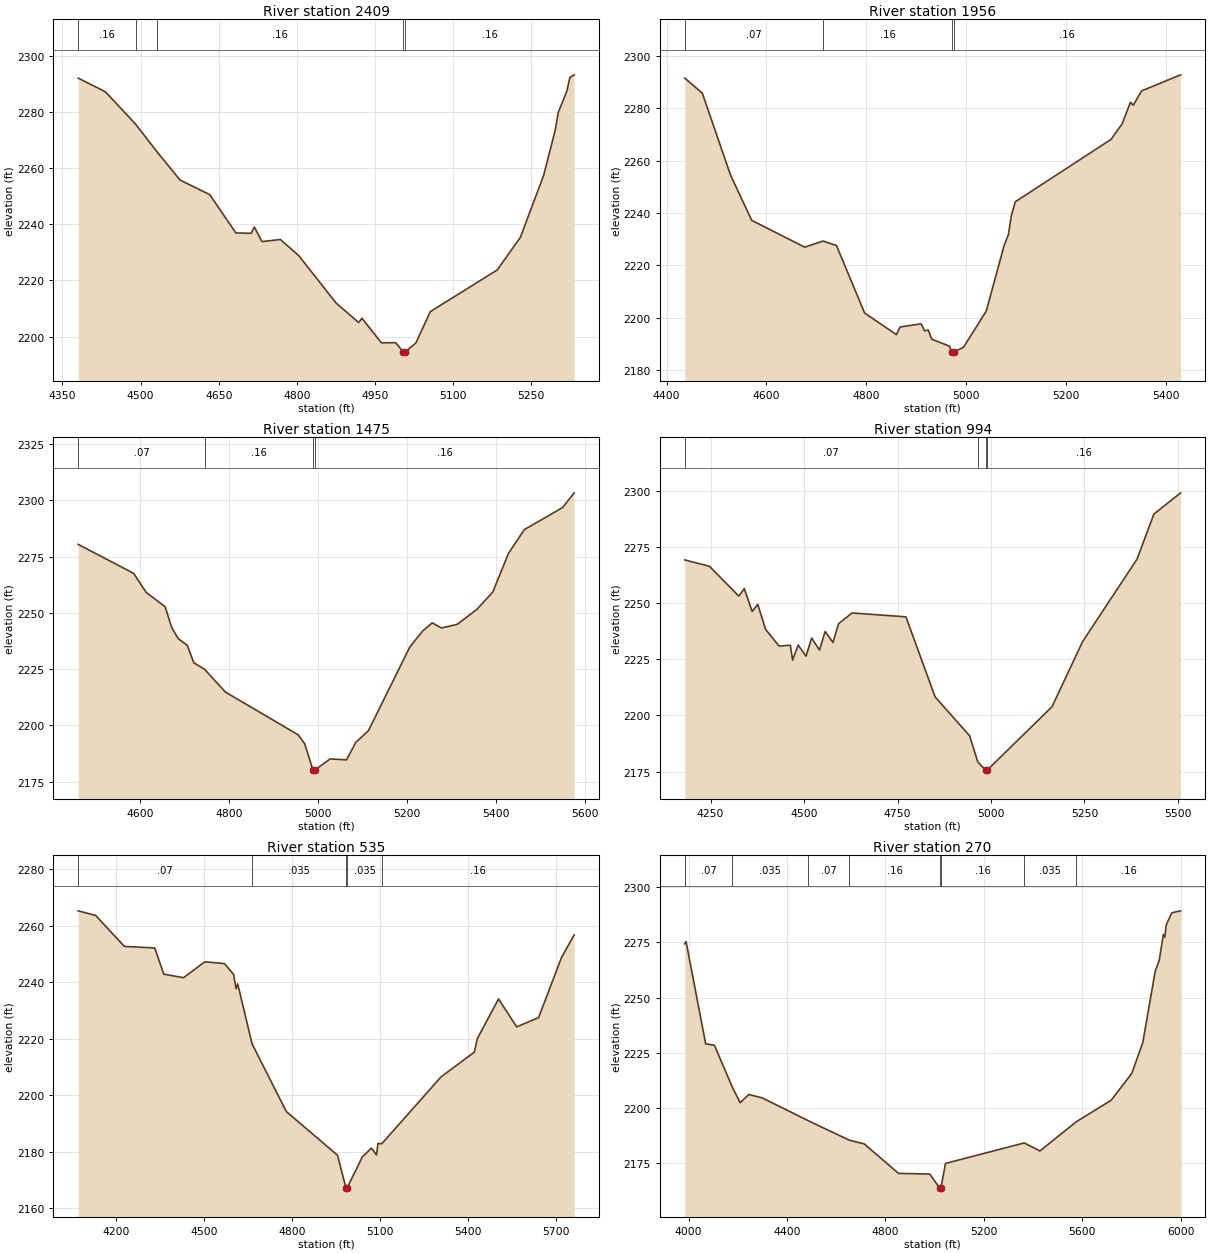
Type RM Length L Ch R = 1,2409,453,453,453
BEGIN DESCRIPTION:
elmc150
END DESCRIPTION:
XS GIS Cut Line= 3
      1498707.98      6779954.14      1499205.28      6779584.55
      1499355.00      6779288.00
#Sta/Elev= 30
  4380.4 2292.00  4432.7 2287.12  4490.4 2275.64  4531.4 2265.84  4576.0 2255.70
  4632.9 2250.52  4683.0 2236.89  4712.2 2236.76  4718.5 2238.97  4733.1 2233.81
  4768.5 2234.55  4804.0 2228.75  4875.1 2211.98  4918.7 2205.00  4924.9 2206.53
  4962.3 2197.79  4989.6 2197.83  5003.9 2194.61  5004.2 2194.11  5008.3 2194.61
  5028.4 2197.72  5056.3 2208.91  5184.5 2223.70  5229.1 2235.36  5273.7 2257.41
  5296.0 2273.56  5301.6 2279.74  5318.3 2287.39  5323.9 2292.21  5332.2 2293.17
#Mann=5,-1,0
  4380.4    0.16       0  4490.4    0.07       0  4531.4    0.16       0
  5003.9    0.07       0  5008.3    0.16       0
Bank Sta=5003.9,5008.3
Exp/Cntr=0.3,0.1

Type RM Length L Ch R = 1,1956,481,481,481
BEGIN DESCRIPTION:
elmc149
END DESCRIPTION:
XS GIS Cut Line= 3
      1499055.02      6780287.98      1499449.89      6779885.70
      1499645.38      6779502.93
#Sta/Elev= 30
  4436.3 2291.60  4471.6 2285.81  4528.2 2254.48  4570.6 2237.18  4676.7 2226.94
  4713.6 2229.27  4740.4 2227.54  4796.9 2201.72  4860.5 2193.50  4867.7 2196.40
  4910.1 2197.63  4917.1 2194.89  4924.2 2195.29  4931.2 2191.75  4966.7 2189.10
  4971.5 2186.92  4971.8 2186.42  4975.9 2186.92  4994.9 2188.67  5040.5 2202.51
  5076.0 2227.42  5084.9 2231.78  5090.5 2238.78  5098.5 2244.27  5290.5 2268.14
  5312.7 2274.11  5329.3 2282.32  5335.0 2281.18  5351.6 2286.66  5429.8 2292.81
#Mann=4,-1,0
  4436.3    0.07       0  4713.6    0.16       0  4971.5    0.07       0
  4975.9    0.16       0
Bank Sta=4971.5,4975.9
Exp/Cntr=0.3,0.1

Type RM Length L Ch R = 1,1475,481,481,481
BEGIN DESCRIPTION:
elmc148
END DESCRIPTION:
XS GIS Cut Line= 3
      1499372.03      6780609.53      1499698.94      6780179.86
      1500035.38      6779712.08
#Sta/Elev= 30
  4460.1 2280.48  4585.1 2267.57  4612.8 2259.20  4655.9 2252.70  4670.4 2243.59
  4684.9 2238.65  4705.8 2235.54  4720.3 2227.85  4744.4 2225.00  4791.0 2214.89
  4955.3 2195.80  4969.8 2191.86  4988.4 2180.19  4988.7 2179.69  4992.9 2180.19
  5026.9 2185.11  5063.9 2184.70  5084.9 2192.51  5113.1 2197.63  5206.4 2234.88
  5235.9 2242.10  5256.8 2245.59  5277.6 2243.31  5313.2 2244.95  5357.4 2251.60
  5393.0 2259.28  5428.6 2276.56  5464.2 2287.07  5550.1 2296.83  5576.2 2303.39
#Mann=4,-1,0
  4460.1    0.07       0  4744.4    0.16       0  4988.4    0.07       0
  4992.9    0.16       0
Bank Sta=4988.4,4992.9
Exp/Cntr=0.3,0.1

Type RM Length L Ch R = 1,994,459,459,459
BEGIN DESCRIPTION:
elmc147
END DESCRIPTION:
XS GIS Cut Line= 3
      1499519.62      6780783.13      1500122.89      6780379.50
      1500244.04      6779791.08
#Sta/Elev= 30
  4180.6 2269.30  4247.0 2266.46  4325.1 2253.21  4340.1 2256.49  4361.1 2246.34
  4376.1 2249.49  4397.1 2238.33  4433.2 2230.92  4463.2 2231.27  4469.2 2224.68
  4484.2 2231.35  4505.2 2226.42  4520.2 2234.50  4541.2 2229.13  4556.3 2237.40
  4577.3 2232.52  4592.3 2240.90  4628.3 2245.67  4772.4 2243.94  4850.5 2208.26
  4942.7 2190.97  4964.8 2179.24  4985.6 2175.70  4986.0 2175.20  4990.2 2175.70
  5163.2 2203.89  5244.9 2232.89  5390.5 2269.62  5435.7 2289.72  5507.2 2299.19
#Mann=4,-1,0
  4180.6    0.07       0  4964.8    0.16       0  4985.6    0.07       0
  4990.2    0.16       0
Bank Sta=4985.6,4990.2
Exp/Cntr=0.3,0.1

Type RM Length L Ch R = 1,535,265,265,265
BEGIN DESCRIPTION:
elmc146
END DESCRIPTION:
XS GIS Cut Line= 4
      1499602.02      6780774.49      1500131.57      6780509.71
      1500458.85      6780436.61      1500639.39      6779698.05
#Sta/Elev= 30
  4072.6 2265.27  4131.8 2263.64  4229.7 2252.68  4333.1 2252.12  4363.8 2242.84
  4430.9 2241.60  4503.6 2247.23  4570.7 2246.58  4601.4 2242.74  4609.8 2237.69
  4615.4 2239.43  4664.2 2218.18  4780.9 2194.19  4955.1 2178.74  4983.5 2167.24
  4983.9 2166.74  4988.1 2167.24  5039.7 2178.20  5070.6 2181.27  5087.6 2178.85
  5092.7 2182.91  5105.6 2182.81  5307.4 2206.49  5420.6 2215.23  5431.0 2220.09
  5503.0 2234.06  5564.8 2224.18  5639.3 2227.47  5717.4 2248.79  5760.3 2256.73
#Mann=5,-1,0
  4072.6    0.07       0  4664.2   0.035       0  4983.5   0.035       0
  4988.1   0.035       0  5105.6    0.16       0
Bank Sta=4983.5,4988.1
Exp/Cntr=0.3,0.1

Type RM Length L Ch R = 1,270,0,0,0
BEGIN DESCRIPTION:
elmc293
END DESCRIPTION:
XS GIS Cut Line= 4
      1499732.26      6780974.12      1500565.60      6780657.28
      1500912.82      6780314.40      1501199.28      6779745.81
#Sta/Elev= 30
  3983.8 2274.38  3989.5 2275.40  4069.2 2229.00  4104.6 2228.38  4178.1 2209.23
  4209.1 2202.31  4244.5 2206.03  4299.4 2204.49  4484.1 2194.25  4653.2 2185.29
  4713.7 2183.62  4853.3 2170.23  4980.5 2169.93  5020.6 2163.60  5021.0 2163.10
  5025.2 2163.60  5044.1 2174.75  5364.2 2184.06  5427.9 2180.41  5575.9 2193.66
  5717.9 2203.45  5801.6 2215.62  5846.2 2229.57  5896.8 2261.98  5913.1 2266.91
  5929.8 2278.61  5935.4 2277.36  5941.6 2282.97  5964.0 2288.44  6000.0 2289.34
#Mann=8,-1,0
  3983.8    0.07       0  4178.1   0.035       0  4484.1    0.07       0
  4653.2    0.16       0  5020.6    0.07       0  5025.2    0.16       0
  5364.2   0.035       0  5575.9    0.16       0
Bank Sta=5020.6,5025.2
Exp/Cntr=0.3,0.1

Chan Stop Cuts=-1