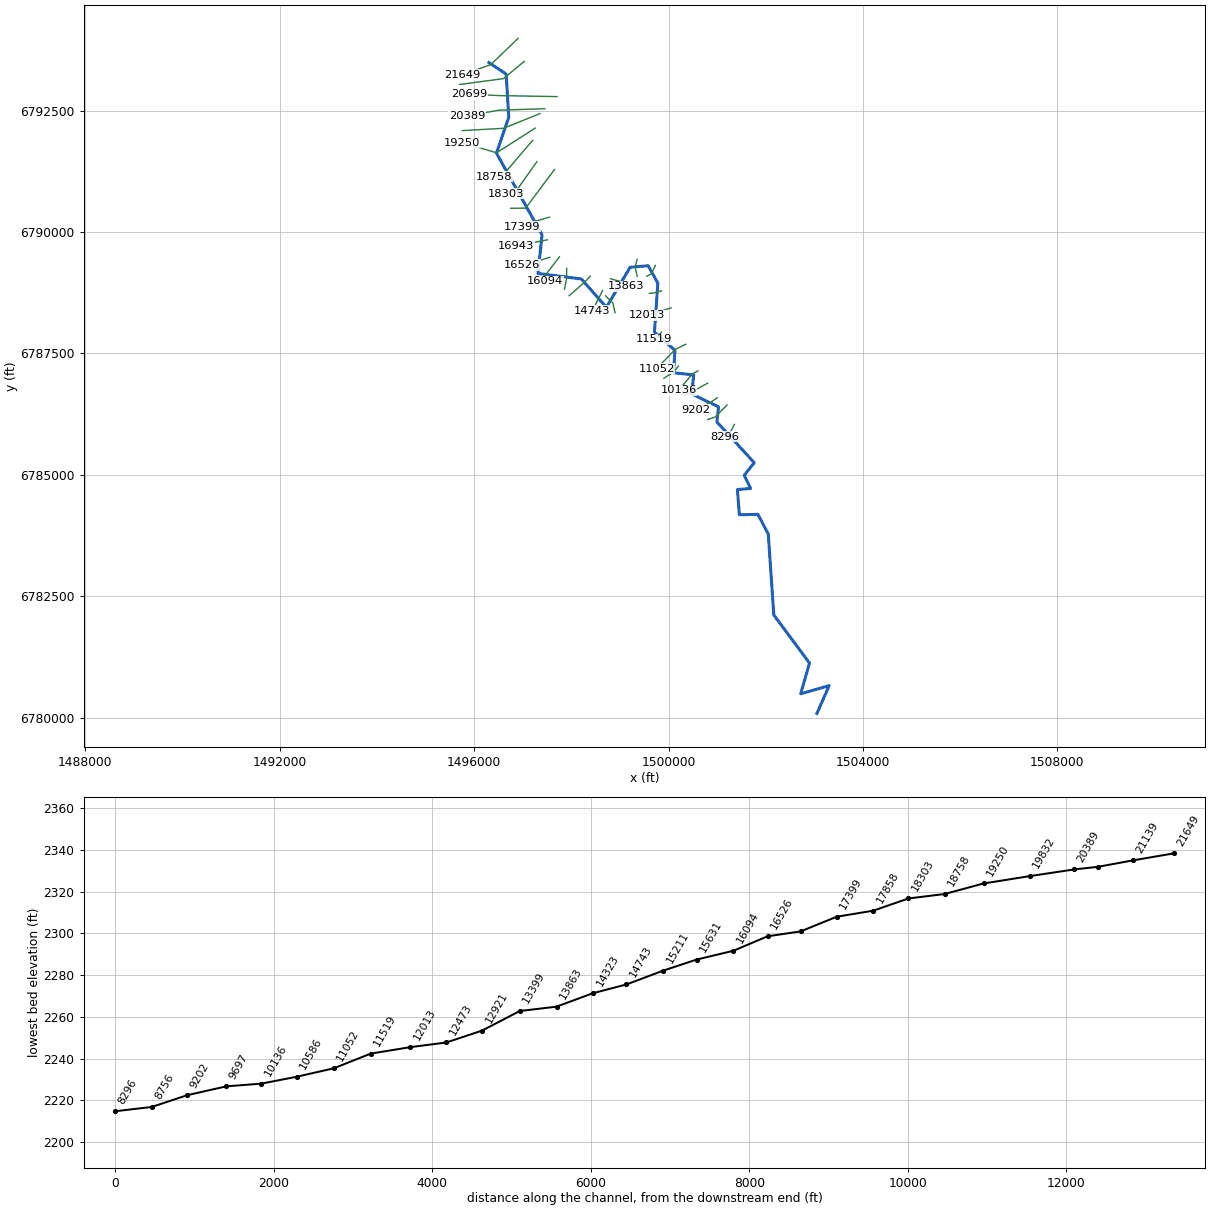
--- Elm 23.prj (project) ---

Proj Title=Elm 23 Base Level Engineering
Current Plan=p01
Default Exp/Contr=0.3,0.1
English Units
Geom File=g01
Flow File=f01
Plan File=p01
BEGIN DESCRIPTION:
Elm 23
END DESCRIPTION:

--- Elm 23.p01 (plan) ---

Plan Title=Multiple Run
Short Identifier=Multiple
Geom File=g01
Flow File=f01
Subcritical Flow
K Sum by GR= 0
Std Step Tol= 0.01
Critical Tol= 0.01
Num of Std Step Trials= 20
Max Error Tol= 0.3
Flow Tol Ratio= 0.001
Split Flow NTrial= 30
Split Flow Tol= 0.02
Split Flow Ratio= 0.02
Log Output Level= 0
Friction Slope Method= 1
Unsteady Friction Slope Method= 2
Unsteady Bridges Friction Slope Method= 1
Parabolic Critical Depth
Global Vel Dist=  1 , 1 , 1
Global Log Level= 0
CheckData=True
Encroach Param= -1, 0, 0, 0
BEGIN DESCRIPTION:
Multiple Run
END DESCRIPTION:

--- Elm 23.f01 (steady flow) ---

Flow Title=Multiple
Number of Profiles=7
Profile Names=10-year,25-year,50-year,1pct_min,100-year,1pct_plu,500-year
River Rch & RM= Elm 23,Reach-1,21649
     314     442     550     424     680     936    1050
River Rch & RM= Elm 23,Reach-1,20699
     400     570     714     554     887    1220    1390
River Rch & RM= Elm 23,Reach-1,18303
     517     746     942     736    1180    1620    1870
River Rch & RM= Elm 23,Reach-1,12473
     646     943    1200     944    1510    2080    2430
River Rch & RM= Elm 23,Reach-1,9202
     742    1090    1390    1100    1760    2420    2850
River Rch & RM= Elm 23,Reach-1,4667
     816    1200    1540    1220    1960    2690    3190
Boundary for River Rch & Prof#=Elm 23,Reach-1,1
Up Type=0
Dn Type=3
Dn Slope=0.005
Boundary for River Rch & Prof#=Elm 23,Reach-1,2
Up Type=0
Dn Type=3
Dn Slope=0.005
Boundary for River Rch & Prof#=Elm 23,Reach-1,3
Up Type=0
Dn Type=3
Dn Slope=0.005
Boundary for River Rch & Prof#=Elm 23,Reach-1,4
Up Type=0
Dn Type=3
Dn Slope=0.005
Boundary for River Rch & Prof#=Elm 23,Reach-1,5
Up Type=0
Dn Type=3
Dn Slope=0.005
Boundary for River Rch & Prof#=Elm 23,Reach-1,6
Up Type=0
Dn Type=3
Dn Slope=0.005
Boundary for River Rch & Prof#=Elm 23,Reach-1,7
Up Type=0
Dn Type=3
Dn Slope=0.005

--- Elm 23.g01 (geometry) ---

Geom Title=Existing Conditions

River Reach=Elm 23,Reach-1
Reach XY= 30
      1496305.00      6793488.00      1496658.65      6793253.28
      1496712.58      6792363.44      1496459.11      6791624.60
      1497397.49      6789941.98      1497313.90      6789146.52
      1498206.44      6789033.26      1498721.47      6788450.82
      1499209.54      6789273.25      1499581.65      6789305.61
      1499780.77      6788945.08      1499710.63      6787939.67
      1500131.50      6787562.22      1500104.78      6787101.26
      1500518.97      6787057.84      1500475.54      6786667.01
      1501029.02      6786399.11      1500995.43      6786089.34
      1501764.25      6785249.61      1501558.98      6784992.09
      1501689.60      6784719.64      1501417.16      6784697.25
      1501458.21      6784178.48      1501838.89      6784185.95
      1502052.81      6783782.09      1502166.80      6782114.04
      1502901.31      6781123.84      1502720.01      6780491.60
      1503305.76      6780658.96      1503055.00      6780088.00

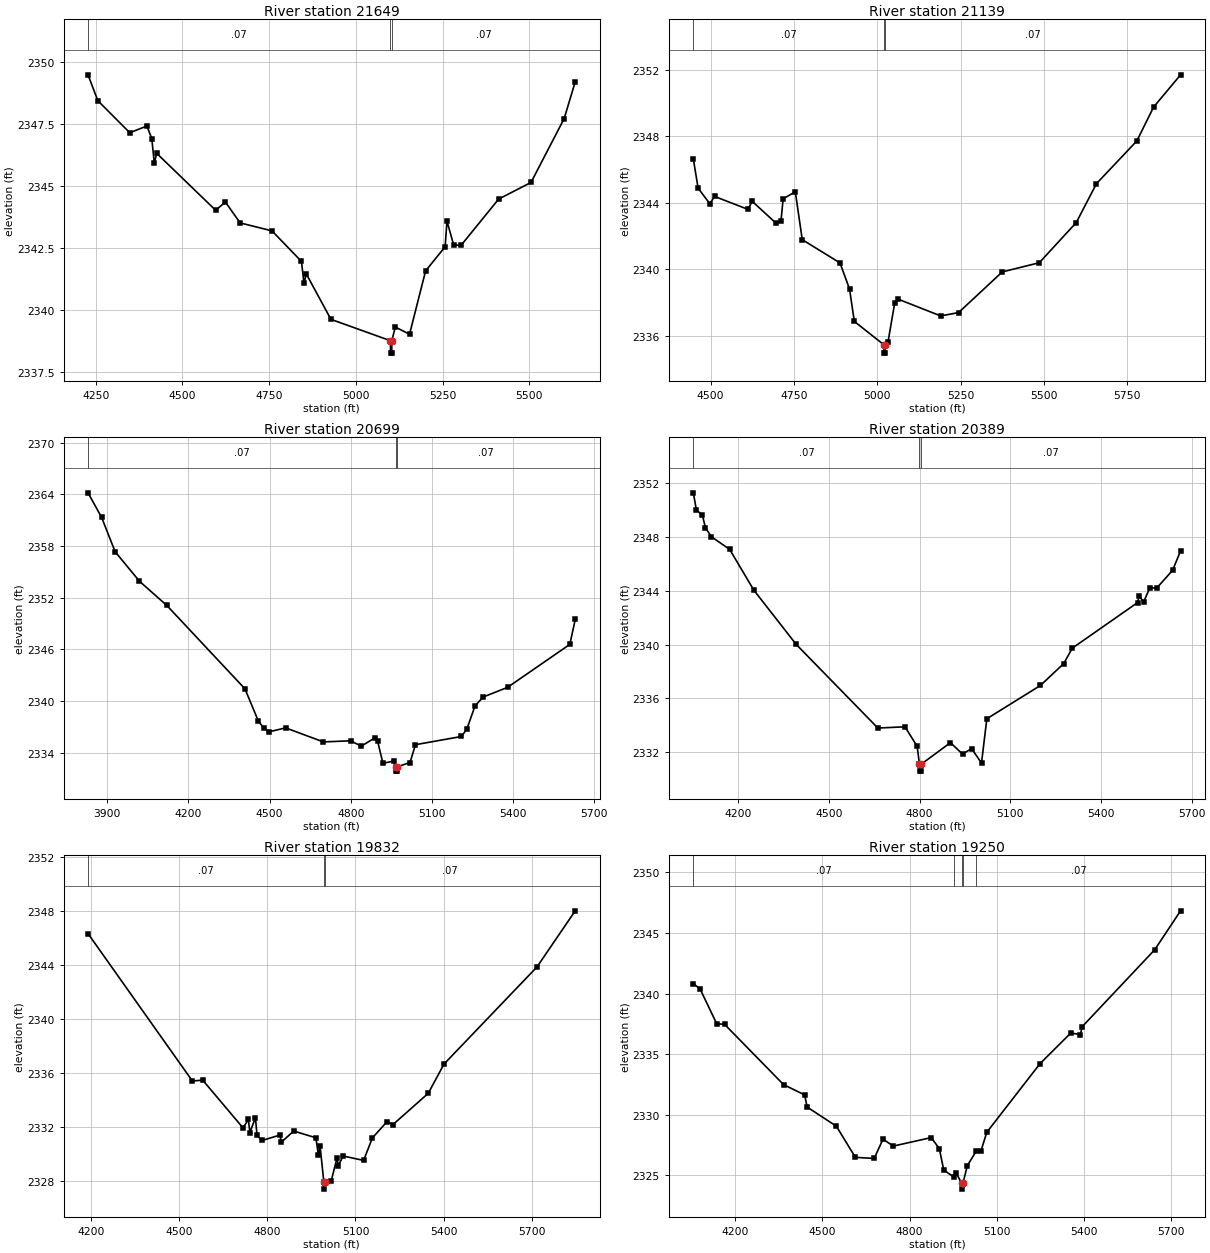
Type RM Length L Ch R = 1,21649,510,510,510
BEGIN DESCRIPTION:
97
END DESCRIPTION:
XS GIS Cut Line= 3
      1496905.00      6793988.00      1496344.90      6793447.75
      1495754.98      6793237.99
#Sta/Elev= 30
  4228.1 2349.47  4256.3 2348.43  4348.4 2347.14  4397.8 2347.41  4411.9 2346.90
  4419.1 2345.92  4426.1 2346.31  4595.9 2344.02  4624.1 2344.35  4666.6 2343.51
  4758.4 2343.19  4843.3 2341.96  4850.5 2341.09  4857.5 2341.45  4928.2 2339.63
  5099.7 2338.77  5100.0 2338.27  5103.5 2338.27  5103.7 2338.77  5113.8 2339.32
  5154.8 2339.03  5201.1 2341.58  5257.4 2342.55  5262.7 2343.58  5282.1 2342.62
  5303.4 2342.61  5411.7 2344.47  5505.0 2345.14  5600.5 2347.71  5632.4 2349.19
#Mann=3,-1,0
  4228.1    0.07       0  5099.7    0.07       0  5103.7    0.07       0
Bank Sta=5099.7,5103.7
Exp/Cntr=0.3,0.1

Type RM Length L Ch R = 1,21139,440,440,440
BEGIN DESCRIPTION:
96
END DESCRIPTION:
XS GIS Cut Line= 3
      1497029.99      6793512.99      1496604.62      6793158.14
      1495704.95      6793037.99
#Sta/Elev= 30
  4448.3 2346.64  4462.6 2344.89  4497.7 2343.95  4512.1 2344.39  4611.1 2343.62
  4625.3 2344.09  4696.9 2342.77  4711.2 2342.91  4717.7 2344.25  4754.2 2344.67
  4775.0 2341.79  4888.2 2340.39  4916.9 2338.82  4931.2 2336.87  5020.0 2335.46
  5020.3 2334.96  5023.8 2334.96  5024.0 2335.46  5032.1 2335.61  5052.3 2337.97
  5062.4 2338.21  5190.3 2337.20  5244.0 2337.40  5375.1 2339.85  5486.1 2340.40
  5597.1 2342.82  5657.6 2345.16  5778.7 2347.73  5829.1 2349.77  5909.9 2351.71
#Mann=3,-1,0
  4448.3    0.07       0  5020.0    0.07       0  5024.0    0.07       0
Bank Sta=5020,5024
Exp/Cntr=0.3,0.1

Type RM Length L Ch R = 1,20699,310,310,310
BEGIN DESCRIPTION:
95
END DESCRIPTION:
XS GIS Cut Line= 3
      1497705.05      6792788.00      1496524.45      6792808.55
      1495905.02      6792838.00
#Sta/Elev= 30
  3828.7 2364.18  3878.8 2361.34  3928.8 2357.35  4018.8 2353.92  4119.9 2351.11
  4408.8 2341.43  4458.8 2337.65  4478.8 2336.88  4498.8 2336.45  4558.9 2336.90
  4698.9 2335.27  4798.9 2335.40  4838.9 2334.78  4888.9 2335.74  4898.9 2335.38
  4918.9 2332.78  4958.9 2333.06  4966.5 2332.38  4966.9 2331.88  4971.0 2331.88
  4971.3 2332.38  5018.9 2332.88  5039.0 2334.95  5209.1 2335.90  5229.2 2336.78
  5259.2 2339.45  5289.2 2340.48  5379.3 2341.60  5609.6 2346.59  5629.6 2349.48
#Mann=3,-1,0
  3828.7    0.07       0  4966.5    0.07       0  4971.3    0.07       0
Bank Sta=4966.5,4971.3
Exp/Cntr=0.3,0.1

Type RM Length L Ch R = 1,20389,557,557,557
BEGIN DESCRIPTION:
94
END DESCRIPTION:
XS GIS Cut Line= 3
      1497455.02      6792538.00      1496504.58      6792508.94
      1495855.03      6792388.00
#Sta/Elev= 30
  4051.8 2351.30  4061.8 2350.03  4081.8 2349.63  4091.8 2348.70  4111.8 2348.02
  4171.9 2347.09  4251.9 2344.05  4392.0 2340.01  4662.1 2333.78  4752.1 2333.87
  4792.2 2332.41  4799.8 2331.07  4800.1 2330.57  4804.2 2330.57  4804.6 2331.07
  4902.2 2332.69  4942.2 2331.84  4972.2 2332.25  5005.0 2331.17  5022.6 2334.47
  5199.8 2336.95  5276.9 2338.58  5305.3 2339.73  5521.0 2343.12  5526.5 2343.60
  5541.4 2343.17  5561.7 2344.23  5584.3 2344.20  5637.1 2345.53  5663.4 2346.97
#Mann=3,-1,0
  4051.8    0.07       0  4799.8    0.07       0  4804.6    0.07       0
Bank Sta=4799.8,4804.6
Exp/Cntr=0.3,0.1

Type RM Length L Ch R = 1,19832,582,582,582
BEGIN DESCRIPTION:
93
END DESCRIPTION:
XS GIS Cut Line= 3
      1497354.96      6792437.98      1496604.88      6792135.45
      1495754.99      6792088.00
#Sta/Elev= 30
  4188.8 2346.35  4544.4 2335.41  4579.4 2335.48  4717.1 2331.93  4735.0 2332.56
  4740.4 2331.59  4759.2 2332.70  4764.6 2331.37  4781.8 2331.00  4842.4 2331.40
  4847.8 2330.88  4889.6 2331.70  4965.1 2331.20  4973.9 2329.89  4979.3 2330.61
  4992.4 2327.89  4992.8 2327.39  4997.2 2327.89  5017.5 2328.01  5037.0 2329.69
  5042.0 2329.13  5057.6 2329.85  5127.7 2329.52  5157.7 2331.19  5207.8 2332.40
  5227.8 2332.18  5348.0 2334.50  5401.7 2336.67  5718.6 2343.88  5848.8 2348.04
#Mann=3,-1,0
  4188.8    0.07       0  4992.4    0.07       0  4997.2    0.07       0
Bank Sta=4992.4,4997.2
Exp/Cntr=0.3,0.1

Type RM Length L Ch R = 1,19250,492,492,492
BEGIN DESCRIPTION:
92
END DESCRIPTION:
XS GIS Cut Line= 3
      1497255.03      6792138.02      1496463.14      6791631.94
      1495755.00      6791838.00
#Sta/Elev= 30
  4055.8 2340.81  4078.7 2340.39  4136.2 2337.51  4163.3 2337.46  4366.3 2332.49
  4439.0 2331.64  4447.5 2330.64  4548.1 2329.06  4613.6 2326.49  4678.4 2326.40
  4708.6 2327.99  4744.2 2327.42  4874.7 2328.12  4902.6 2327.21  4917.8 2325.45
  4952.8 2324.86  4960.1 2325.23  4979.1 2324.37  4979.4 2323.87  4984.0 2324.37
  4999.1 2325.81  5030.5 2327.03  5045.7 2327.00  5066.1 2328.56  5249.4 2334.22
  5355.1 2336.74  5388.6 2336.62  5393.8 2337.25  5644.1 2343.61  5733.1 2346.82
#Mann=5,-1,0
  4055.8    0.07       0  4952.8    0.16       0  4979.1    0.07       0
  4984.0    0.16       0  5030.5    0.07       0
Bank Sta=4979.1,4984
Exp/Cntr=0.3,0.1

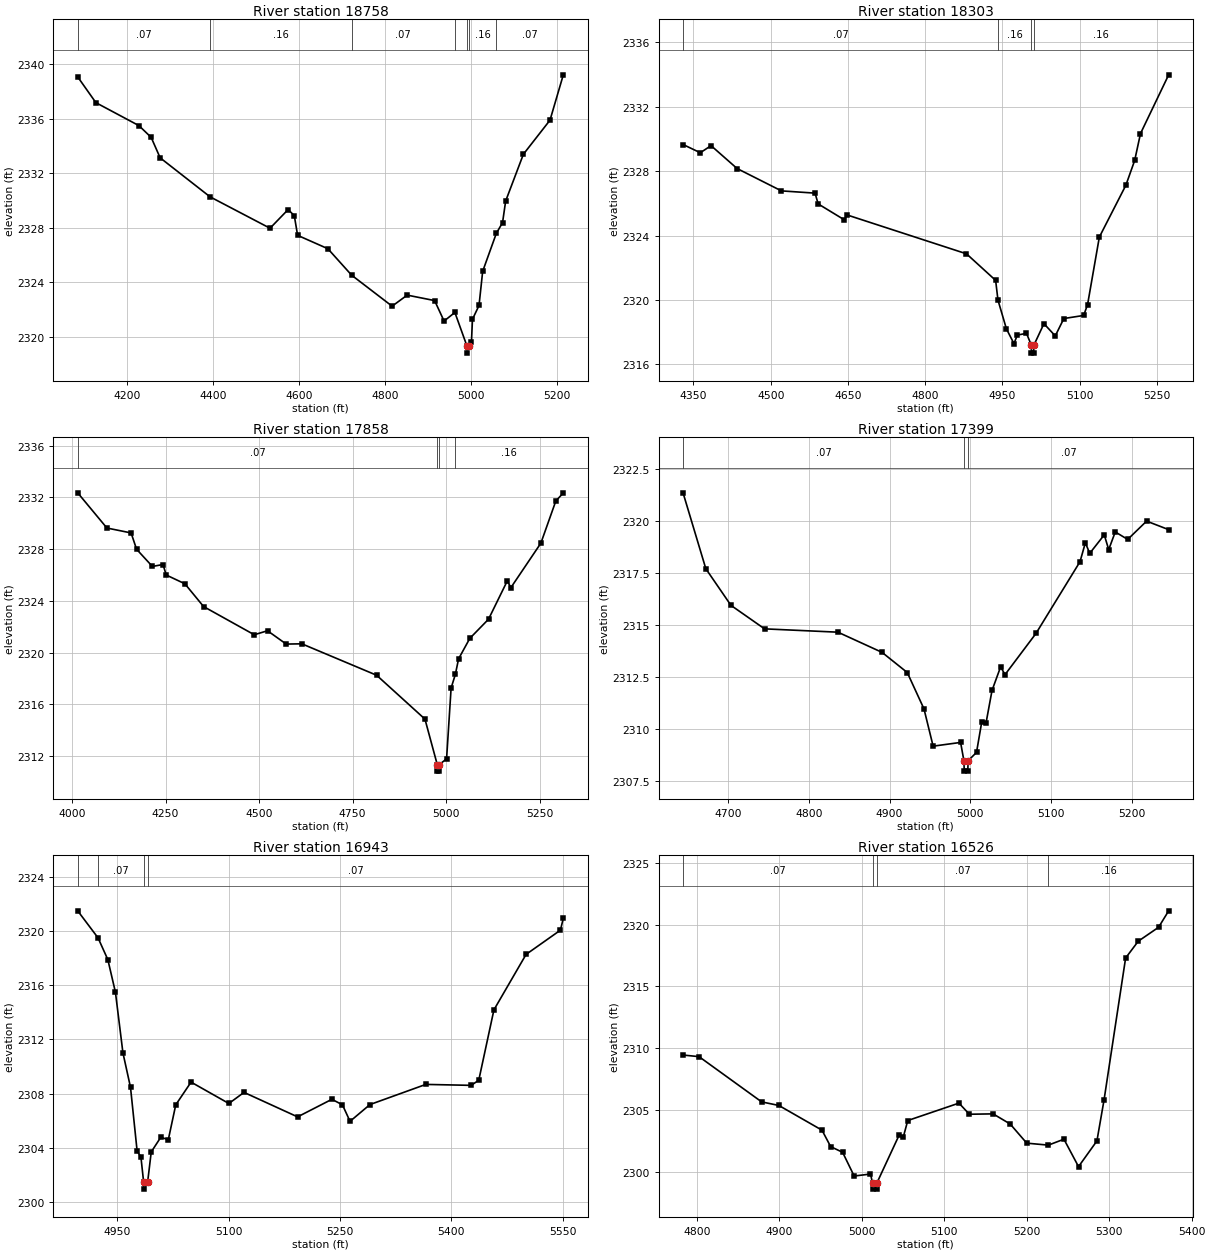
Type RM Length L Ch R = 1,18758,455,455,455
BEGIN DESCRIPTION:
91
END DESCRIPTION:
XS GIS Cut Line= 3
      1497205.00      6791888.00      1496608.87      6791189.40
      1496405.02      6791138.01
#Sta/Elev= 30
  4085.9 2339.06  4128.2 2337.17  4228.1 2335.49  4256.6 2334.63  4277.5 2333.13
  4393.6 2330.27  4532.9 2327.97  4575.0 2329.34  4589.3 2328.89  4597.0 2327.45
  4667.3 2326.47  4722.6 2324.53  4816.6 2322.26  4851.7 2323.07  4915.4 2322.67
  4937.4 2321.17  4962.5 2321.80  4990.8 2319.32  4991.2 2318.82  4995.8 2319.32
  5001.0 2319.62  5003.4 2321.30  5018.6 2322.31  5027.1 2324.81  5058.9 2327.60
  5073.3 2328.38  5080.5 2329.96  5121.7 2333.39  5183.6 2335.89  5214.5 2339.21
#Mann=7,-1,0
  4085.9    0.07       0  4393.6    0.16       0  4722.6    0.07       0
  4962.5    0.16       0  4990.8    0.07       0  4995.8    0.16       0
  5058.9    0.07       0
Bank Sta=4990.8,4995.8
Exp/Cntr=0.3,0.1

Type RM Length L Ch R = 1,18303,445,445,445
BEGIN DESCRIPTION:
90
END DESCRIPTION:
XS GIS Cut Line= 3
      1497291.23      6791447.70      1496905.79      6790903.44
      1496655.01      6790788.00
#Sta/Elev= 30
  4329.8 2329.66  4363.3 2329.15  4384.2 2329.59  4434.7 2328.17  4520.8 2326.78
  4586.1 2326.64  4592.2 2325.97  4642.6 2324.99  4648.8 2325.28  4880.2 2322.87
  4936.8 2321.22  4941.3 2320.00  4957.7 2318.21  4972.4 2317.29  4978.9 2317.82
  4996.7 2317.93  5006.1 2317.20  5006.4 2316.70  5010.8 2316.70  5011.2 2317.20
  5030.6 2318.53  5052.6 2317.77  5069.3 2318.85  5107.7 2319.04  5115.3 2319.71
  5138.2 2323.91  5189.7 2327.13  5206.8 2328.67  5218.1 2330.34  5272.8 2333.99
#Mann=4,-1,0
  4329.8    0.07       0  4941.3    0.16       0  5006.1    0.07       0
  5011.2    0.16       0
Bank Sta=5006.1,5011.2
Exp/Cntr=0.3,0.1

Type RM Length L Ch R = 1,17858,459,459,459
BEGIN DESCRIPTION:
89
END DESCRIPTION:
XS GIS Cut Line= 3
      1497654.99      6791287.99      1497060.59      6790492.79
      1496755.03      6790488.00
#Sta/Elev= 30
  4015.1 2332.35  4093.2 2329.63  4157.9 2329.25  4172.5 2327.99  4214.8 2326.66
  4243.3 2326.81  4251.7 2326.00  4301.7 2325.32  4351.7 2323.56  4487.2 2321.38
  4522.6 2321.69  4572.6 2320.66  4614.4 2320.68  4814.4 2318.25  4943.6 2314.86
  4976.5 2311.34  4976.9 2310.84  4981.3 2310.84  4981.7 2311.34  5001.4 2311.79
  5013.5 2317.26  5024.8 2318.31  5033.5 2319.52  5063.5 2321.10  5113.5 2322.58
  5163.5 2325.53  5173.5 2325.03  5253.5 2328.46  5293.5 2331.72  5313.5 2332.34
#Mann=4,-1,0
  4015.1    0.07       0  4976.5    0.07       0  4981.7    0.07       0
  5024.8    0.16       0
Bank Sta=4976.5,4981.7
Exp/Cntr=0.3,0.1

Type RM Length L Ch R = 1,17399,456,456,456
BEGIN DESCRIPTION:
88
END DESCRIPTION:
XS GIS Cut Line= 3
      1497552.13      6790305.49      1497205.12      6790208.05
      1496984.37      6790112.42
#Sta/Elev= 30
  4644.4 2321.35  4672.6 2317.70  4703.7 2315.94  4745.3 2314.81  4836.1 2314.65
  4890.7 2313.68  4921.9 2312.71  4942.6 2310.96  4953.9 2309.17  4987.9 2309.35
  4992.0 2308.47  4992.4 2307.97  4996.8 2307.97  4997.2 2308.47  5007.6 2308.87
  5014.0 2310.32  5019.4 2310.29  5026.8 2311.85  5037.4 2312.98  5042.9 2312.61
  5081.2 2314.59  5135.7 2318.04  5142.3 2318.95  5147.7 2318.44  5165.7 2319.33
  5171.2 2318.62  5179.3 2319.47  5194.7 2319.11  5218.1 2319.99  5245.4 2319.58
#Mann=3,-1,0
  4644.4    0.07       0  4992.0    0.07       0  4997.2    0.07       0
Bank Sta=4992,4997.2
Exp/Cntr=0.3,0.1

Type RM Length L Ch R = 1,16943,417,417,417
BEGIN DESCRIPTION:
87
END DESCRIPTION:
XS GIS Cut Line= 3
      1497504.96      6789837.99      1497405.12      6789819.86
      1496863.37      6789712.81
#Sta/Elev= 30
  4896.9 2321.51  4924.3 2319.51  4937.5 2317.90  4947.7 2315.49  4957.8 2311.01
  4968.0 2308.46  4976.9 2303.75  4982.0 2303.32  4985.7 2301.44  4986.1 2300.94
  4991.0 2301.44  4995.9 2303.69  5008.7 2304.77  5018.9 2304.60  5028.9 2307.17
  5049.5 2308.85  5100.4 2307.27  5120.8 2308.09  5192.9 2306.28  5239.1 2307.58
  5253.3 2307.17  5263.5 2305.95  5290.3 2307.19  5365.5 2308.68  5426.6 2308.61
  5436.8 2308.99  5457.2 2314.19  5500.5 2318.29  5546.7 2320.08  5550.6 2320.95
#Mann=4,-1,0
  4896.9    0.16       0  4924.3    0.07       0  4985.7    0.07       0
  4991.0    0.07       0
Bank Sta=4985.7,4991
Exp/Cntr=0.3,0.1

Type RM Length L Ch R = 1,16526,432,432,432
BEGIN DESCRIPTION:
86
END DESCRIPTION:
XS GIS Cut Line= 3
      1497556.08      6789479.44      1497355.35      6789417.85
      1496989.40      6789319.49
#Sta/Elev= 30
  4783.2 2309.44  4802.6 2309.31  4878.5 2305.65  4899.4 2305.36  4951.7 2303.36
  4962.2 2302.03  4976.7 2301.57  4990.7 2299.65  5010.5 2299.81  5013.0 2299.09
  5013.4 2298.59  5017.9 2298.59  5018.3 2299.09  5045.3 2302.97  5050.4 2302.83
  5055.7 2304.14  5117.8 2305.55  5130.4 2304.65  5159.2 2304.68  5179.9 2303.86
  5200.0 2302.31  5226.2 2302.15  5245.1 2302.63  5262.8 2300.41  5285.1 2302.49
  5293.8 2305.83  5319.9 2317.29  5335.2 2318.65  5359.9 2319.78  5372.1 2321.11
#Mann=4,-1,0
  4783.2    0.07       0  5013.0    0.07       0  5018.3    0.07       0
  5226.2    0.16       0
Bank Sta=5013,5018.3
Exp/Cntr=0.3,0.1

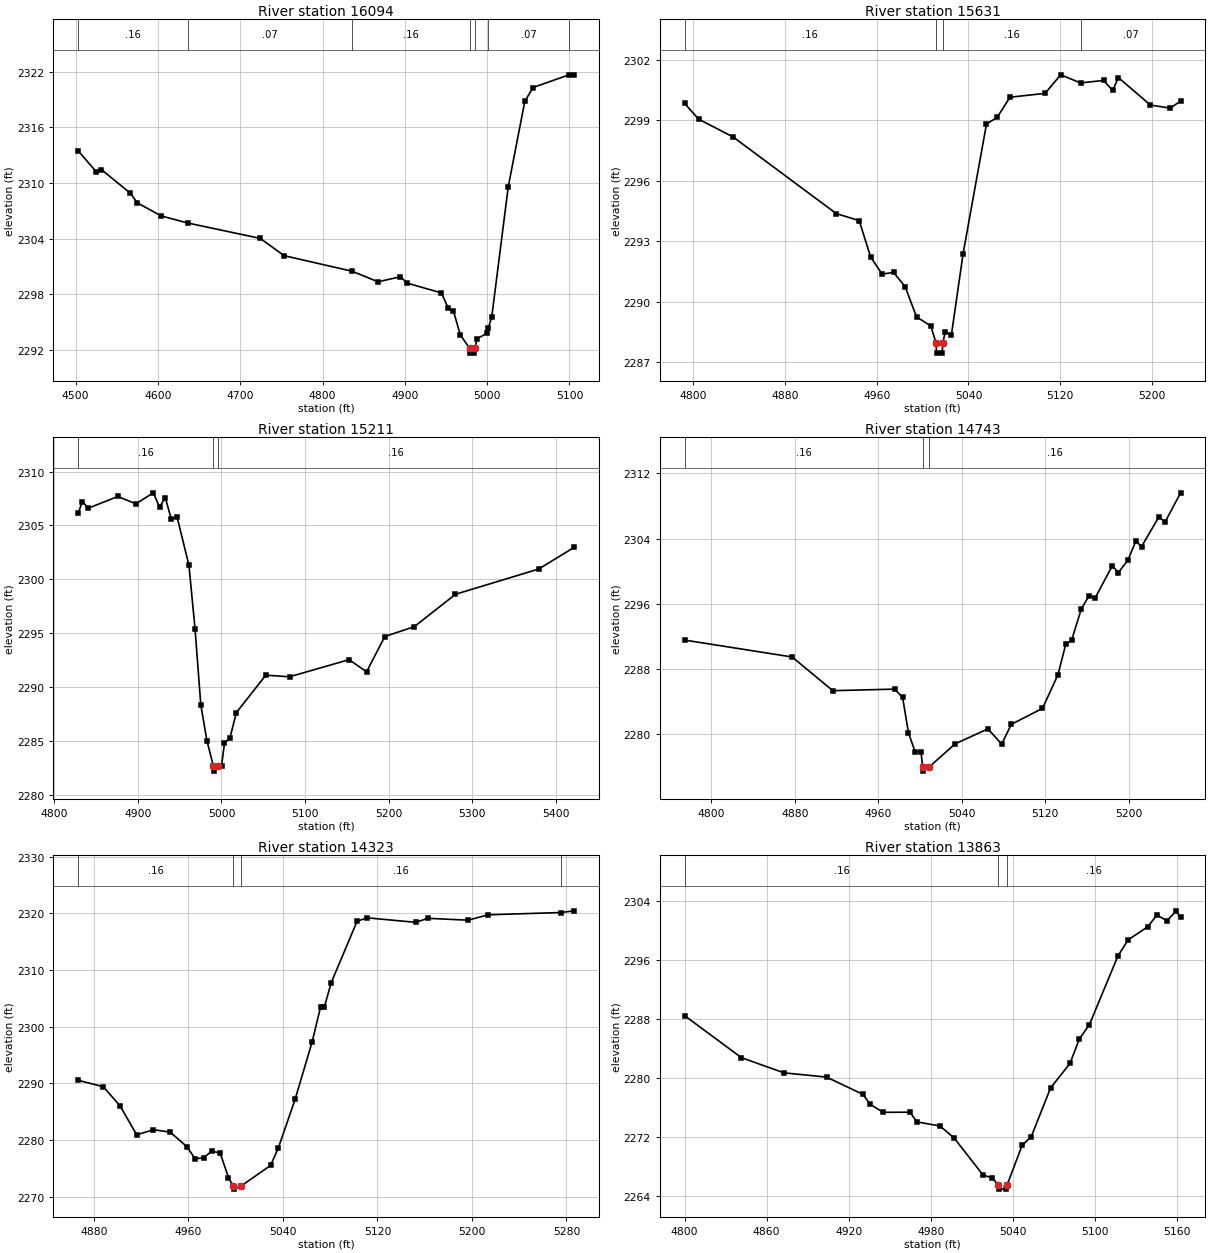
Type RM Length L Ch R = 1,16094,463,463,463
BEGIN DESCRIPTION:
85
END DESCRIPTION:
XS GIS Cut Line= 3
      1497754.99      6789487.98      1497452.81      6789094.11
      1497455.00      6788987.96
#Sta/Elev= 30
  4503.1 2313.46  4524.9 2311.22  4531.2 2311.45  4566.5 2308.89  4574.7 2307.87
  4603.7 2306.45  4636.3 2305.68  4724.3 2304.02  4753.3 2302.16  4835.9 2300.48
  4867.5 2299.34  4894.6 2299.89  4902.8 2299.20  4944.5 2298.14  4952.7 2296.48
  4959.0 2296.21  4967.2 2293.65  4978.8 2292.15  4979.3 2291.65  4984.2 2291.65
  4984.7 2292.15  4988.0 2293.21  4999.5 2293.78  5001.6 2294.40  5005.6 2295.57
  5025.6 2309.58  5045.7 2318.79  5055.7 2320.29  5099.5 2321.66  5105.7 2321.62
#Mann=7,-1,0
  4503.1    0.16       0  4636.3    0.07       0  4835.9    0.16       0
  4978.8    0.07       0  4984.7    0.16       0  5001.6    0.07       0
  5099.5    0.16       0
Bank Sta=4978.8,4984.7
Exp/Cntr=0.3,0.1

Type RM Length L Ch R = 1,15631,420,420,420
BEGIN DESCRIPTION:
84
END DESCRIPTION:
XS GIS Cut Line= 3
      1497903.87      6789250.19      1497902.98      6789038.08
      1497858.59      6788822.21
#Sta/Elev= 30
  4792.5 2299.83  4804.7 2299.05  4834.7 2298.17  4924.7 2294.37  4944.7 2294.02
  4954.7 2292.21  4964.7 2291.37  4974.7 2291.45  4984.7 2290.75  4994.7 2289.25
  5007.2 2288.79  5011.7 2287.95  5012.2 2287.45  5017.1 2287.45  5017.6 2287.95
  5019.7 2288.50  5025.1 2288.35  5035.3 2292.38  5055.7 2298.81  5065.0 2299.14
  5076.2 2300.14  5106.8 2300.33  5120.4 2301.25  5137.7 2300.85  5157.8 2300.97
  5165.7 2300.48  5170.8 2301.11  5198.7 2299.75  5216.0 2299.60  5225.0 2299.95
#Mann=4,-1,0
  4792.5    0.16       0  5011.7    0.07       0  5017.6    0.16       0
  5137.7    0.07       0
Bank Sta=5011.7,5017.6
Exp/Cntr=0.3,0.1

Type RM Length L Ch R = 1,15211,468,468,468
BEGIN DESCRIPTION:
83
END DESCRIPTION:
XS GIS Cut Line= 3
      1498390.04      6789090.15      1498274.95      6788967.66
      1497955.02      6788688.01
#Sta/Elev= 30
  4828.7 2306.12  4833.6 2307.21  4840.9 2306.60  4876.1 2307.68  4897.6 2307.00
  4918.6 2308.02  4925.9 2306.68  4932.8 2307.58  4940.1 2305.55  4946.9 2305.78
  4961.1 2301.29  4968.4 2295.38  4975.3 2288.32  4982.6 2285.01  4990.2 2282.68
  4990.7 2282.18  4996.1 2282.68  5000.1 2282.68  5003.6 2284.77  5010.2 2285.29
  5017.8 2287.61  5053.0 2291.09  5081.4 2290.94  5152.6 2292.53  5173.5 2291.40
  5195.3 2294.68  5230.5 2295.59  5279.8 2298.60  5379.5 2300.95  5421.7 2302.96
#Mann=3,-1,0
  4828.7    0.16       0  4990.2    0.07       0  4996.1    0.16       0
Bank Sta=4990.2,4996.1
Exp/Cntr=0.3,0.1

Type RM Length L Ch R = 1,14743,420,420,420
BEGIN DESCRIPTION:
82
END DESCRIPTION:
XS GIS Cut Line= 3
      1498644.95      6788797.66      1498544.21      6788597.66
      1498431.56      6788372.84
#Sta/Elev= 30
  4774.5 2291.57  4877.5 2289.50  4916.5 2285.37  4975.7 2285.56  4983.4 2284.55
  4989.0 2280.21  4995.4 2277.88  5001.0 2277.88  5002.7 2276.01  5003.2 2275.51
  5008.8 2276.01  5033.7 2278.85  5065.2 2280.69  5078.4 2278.81  5087.5 2281.24
  5117.5 2283.20  5132.3 2287.31  5139.8 2291.06  5145.4 2291.56  5154.6 2295.35
  5162.2 2297.03  5167.8 2296.70  5184.5 2300.69  5190.1 2299.83  5199.4 2301.37
  5206.9 2303.69  5212.5 2303.04  5229.2 2306.70  5234.8 2306.00  5249.9 2309.62
#Mann=3,-1,0
  4774.5    0.16       0  5002.7    0.07       0  5008.8    0.16       0
Bank Sta=5002.7,5008.8
Exp/Cntr=0.3,0.1

Type RM Length L Ch R = 1,14323,460,460,460
BEGIN DESCRIPTION:
81
END DESCRIPTION:
XS GIS Cut Line= 4
      1498705.00      6788688.00      1498801.17      6788589.58
      1498854.90      6788543.65      1498899.16      6788336.83
#Sta/Elev= 30
  4866.7 2290.54  4887.9 2289.42  4902.1 2286.04  4916.2 2280.93  4930.4 2281.83
  4944.5 2281.41  4958.6 2278.86  4965.6 2276.72  4972.8 2276.85  4979.8 2278.08
  4986.9 2277.68  4993.9 2273.39  4998.0 2271.85  4998.5 2271.35  5004.2 2271.85
  5029.5 2275.52  5036.0 2278.55  5050.3 2287.19  5064.6 2297.24  5071.8 2303.43
  5075.0 2303.43  5080.8 2307.74  5102.8 2318.62  5111.4 2319.20  5152.4 2318.41
  5162.6 2319.12  5196.7 2318.79  5213.7 2319.74  5275.1 2320.14  5286.5 2320.44
#Mann=4,-1,0
  4866.7    0.16       0  4998.0    0.07       0  5004.2    0.16       0
  5275.1    0.07       0
Bank Sta=4998,5004.2
Exp/Cntr=0.3,0.1

Type RM Length L Ch R = 1,13863,464,464,464
BEGIN DESCRIPTION:
80
END DESCRIPTION:
XS GIS Cut Line= 3
      1498804.98      6789038.01      1499007.33      6788982.03
      1499120.58      6788879.23
#Sta/Elev= 30
  4800.0 2288.43  4841.5 2282.74  4872.6 2280.68  4903.8 2280.10  4930.5 2277.75
  4935.7 2276.42  4945.3 2275.32  4964.8 2275.34  4970.0 2274.02  4986.8 2273.47
  4997.2 2271.83  5018.5 2266.77  5025.2 2266.45  5029.5 2265.40  5030.0 2264.90
  5035.3 2264.90  5035.8 2265.40  5046.9 2270.83  5053.6 2272.02  5067.8 2278.65
  5082.0 2281.96  5088.7 2285.24  5096.2 2287.23  5117.1 2296.57  5124.6 2298.74
  5138.8 2300.49  5145.5 2302.08  5153.0 2301.31  5159.7 2302.66  5162.9 2301.77
#Mann=3,-1,0
  4800.0    0.16       0  5029.5    0.07       0  5035.8    0.16       0
Bank Sta=5029.5,5035.8
Exp/Cntr=0.3,0.1

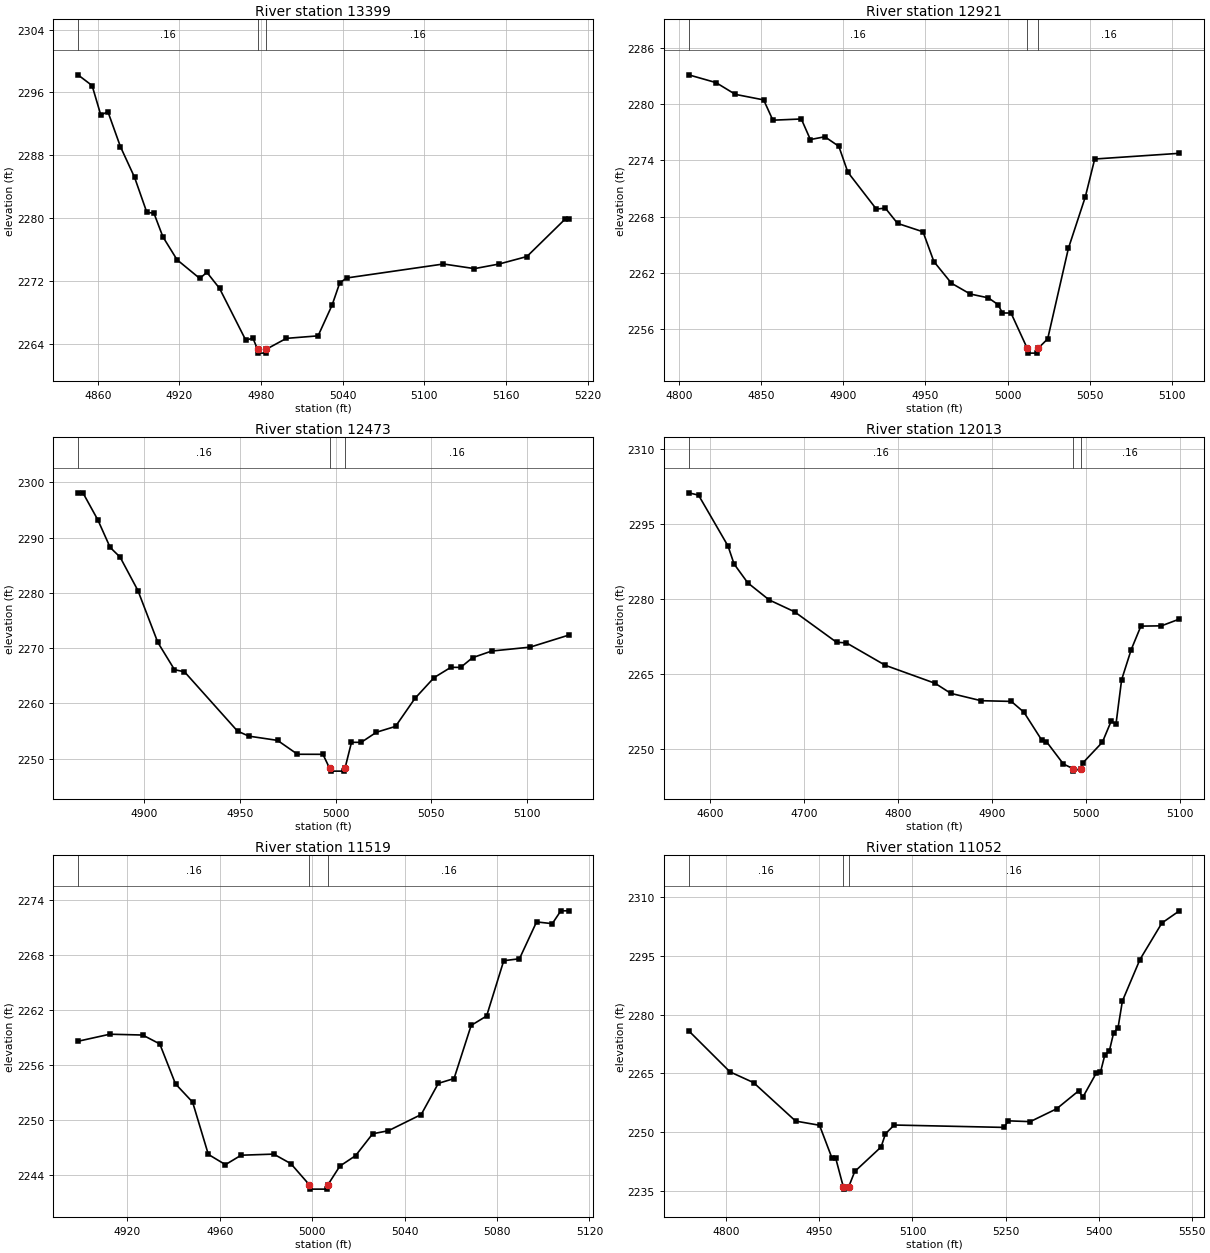
Type RM Length L Ch R = 1,13399,478,478,478
BEGIN DESCRIPTION:
79
END DESCRIPTION:
XS GIS Cut Line= 3
      1499354.99      6789437.95      1499312.17      6789288.53
      1499355.00      6789087.99
#Sta/Elev= 30
  4845.5 2298.25  4855.9 2296.88  4862.3 2293.12  4867.5 2293.56  4876.7 2289.10
  4887.1 2285.19  4896.1 2280.73  4901.3 2280.64  4907.9 2277.62  4918.3 2274.70
  4935.0 2272.32  4940.2 2273.10  4949.5 2271.06  4968.8 2264.45  4974.0 2264.73
  4977.4 2263.31  4977.9 2262.81  4983.4 2262.81  4983.9 2263.31  4998.6 2264.69
  5021.9 2265.01  5032.2 2268.93  5037.8 2271.75  5042.9 2272.38  5114.0 2274.16
  5136.8 2273.57  5154.9 2274.16  5175.3 2275.11  5203.4 2279.88  5206.0 2279.88
#Mann=3,-1,0
  4845.5    0.16       0  4977.4    0.07       0  4983.9    0.16       0
Bank Sta=4977.4,4983.9
Exp/Cntr=0.3,0.1

Type RM Length L Ch R = 1,12921,448,448,448
BEGIN DESCRIPTION:
78
END DESCRIPTION:
XS GIS Cut Line= 3
      1499730.00      6789313.01      1499648.97      6789140.22
      1499554.96      6789087.98
#Sta/Elev= 30
  4806.0 2283.15  4822.6 2282.32  4834.4 2281.06  4851.6 2280.47  4857.2 2278.30
  4874.5 2278.43  4880.0 2276.23  4888.8 2276.53  4897.3 2275.51  4902.8 2272.74
  4920.1 2268.80  4925.6 2268.90  4933.0 2267.27  4948.5 2266.37  4955.1 2263.19
  4965.8 2260.87  4977.2 2259.72  4988.2 2259.31  4994.1 2258.59  4996.8 2257.69
  5002.0 2257.69  5011.9 2253.90  5012.4 2253.40  5017.9 2253.40  5018.4 2253.90
  5024.3 2254.92  5036.9 2264.60  5047.2 2270.11  5052.9 2274.15  5104.4 2274.76
#Mann=3,-1,0
  4806.0    0.16       0  5011.9    0.07       0  5018.4    0.16       0
Bank Sta=5011.9,5018.4
Exp/Cntr=0.3,0.1

Type RM Length L Ch R = 1,12473,460,460,460
BEGIN DESCRIPTION:
77
END DESCRIPTION:
XS GIS Cut Line= 3
      1499855.04      6788788.01      1499715.85      6788747.65
      1499604.99      6788738.00
#Sta/Elev= 30
  4865.5 2298.09  4868.1 2298.09  4875.9 2293.18  4882.3 2288.22  4887.5 2286.46
  4896.8 2280.42  4907.2 2271.03  4915.9 2266.10  4921.1 2265.72  4948.8 2254.99
  4954.7 2254.08  4969.7 2253.31  4980.1 2250.80  4993.4 2250.79  4996.9 2248.25
  4997.4 2247.75  5004.4 2247.75  5004.9 2248.25  5008.3 2252.96  5013.4 2252.96
  5021.3 2254.78  5031.3 2255.84  5041.4 2260.89  5051.4 2264.66  5060.2 2266.53
  5065.3 2266.51  5071.5 2268.27  5081.5 2269.47  5101.6 2270.18  5121.7 2272.35
#Mann=3,-1,0
  4865.5    0.16       0  4996.9    0.07       0  5004.9    0.16       0
Bank Sta=4996.9,5004.9
Exp/Cntr=0.3,0.1

Type RM Length L Ch R = 1,12013,494,494,494
BEGIN DESCRIPTION:
76
END DESCRIPTION:
XS GIS Cut Line= 3
      1500054.96      6788437.99      1499655.30      6788310.59
      1499554.98      6788288.00
#Sta/Elev= 30
  4577.1 2301.16  4587.6 2300.70  4619.0 2290.51  4625.4 2286.93  4640.0 2283.15
  4662.8 2279.73  4689.8 2277.36  4734.5 2271.26  4745.0 2271.14  4786.4 2266.65
  4839.4 2263.05  4856.1 2261.04  4888.3 2259.57  4920.5 2259.43  4933.9 2257.27
  4952.7 2251.74  4957.9 2251.38  4975.9 2246.91  4986.1 2245.98  4986.6 2245.48
  4994.2 2245.98  4996.6 2247.12  5017.4 2251.26  5026.8 2255.49  5031.9 2254.86
  5037.9 2263.76  5048.1 2269.79  5058.4 2274.49  5080.3 2274.55  5099.4 2275.90
#Mann=3,-1,0
  4577.1    0.16       0  4986.1    0.07       0  4994.2    0.16       0
Bank Sta=4986.1,4994.2
Exp/Cntr=0.3,0.1

Type RM Length L Ch R = 1,11519,467,467,467
BEGIN DESCRIPTION:
75
END DESCRIPTION:
XS GIS Cut Line= 3
      1499854.97      6787937.97      1499782.99      6787859.52
      1499704.99      6787787.99
#Sta/Elev= 30
  4898.7 2258.56  4912.5 2259.33  4926.7 2259.24  4934.1 2258.27  4940.9 2253.91
  4948.3 2251.92  4955.1 2246.22  4962.5 2245.10  4969.3 2246.13  4983.4 2246.25
  4990.8 2245.21  4998.7 2242.93  4999.2 2242.43  5006.4 2242.43  5006.9 2242.93
  5012.0 2244.94  5018.8 2246.08  5026.2 2248.47  5033.0 2248.80  5047.2 2250.57
  5054.6 2253.97  5061.4 2254.49  5068.8 2260.29  5075.5 2261.32  5082.9 2267.35
  5089.7 2267.56  5097.1 2271.58  5103.9 2271.39  5107.6 2272.79  5111.0 2272.79
#Mann=3,-1,0
  4898.7    0.16       0  4998.7    0.07       0  5006.9    0.16       0
Bank Sta=4998.7,5006.9
Exp/Cntr=0.3,0.1

Type RM Length L Ch R = 1,11052,466,466,466
BEGIN DESCRIPTION:
74
END DESCRIPTION:
XS GIS Cut Line= 3
      1500354.99      6787688.00      1500143.33      6787586.07
      1499755.02      6787188.02
#Sta/Elev= 30
  4739.3 2275.90  4805.9 2265.38  4843.9 2262.63  4911.7 2252.79  4950.2 2251.72
  4970.5 2243.24  4976.4 2243.24  4988.7 2235.88  4989.2 2235.38  4997.0 2235.88
  5007.0 2239.89  5049.5 2246.17  5056.5 2249.54  5070.6 2251.78  5247.5 2251.17
  5254.5 2252.85  5289.9 2252.65  5332.4 2255.93  5367.7 2260.50  5374.8 2258.94
  5396.0 2264.99  5403.1 2265.30  5410.1 2269.72  5417.3 2270.68  5424.2 2275.32
  5431.4 2276.67  5438.4 2283.50  5466.7 2294.12  5502.1 2303.47  5530.3 2306.58
#Mann=3,-1,0
  4739.3    0.16       0  4988.7    0.07       0  4997.0    0.16       0
Bank Sta=4988.7,4997
Exp/Cntr=0.3,0.1

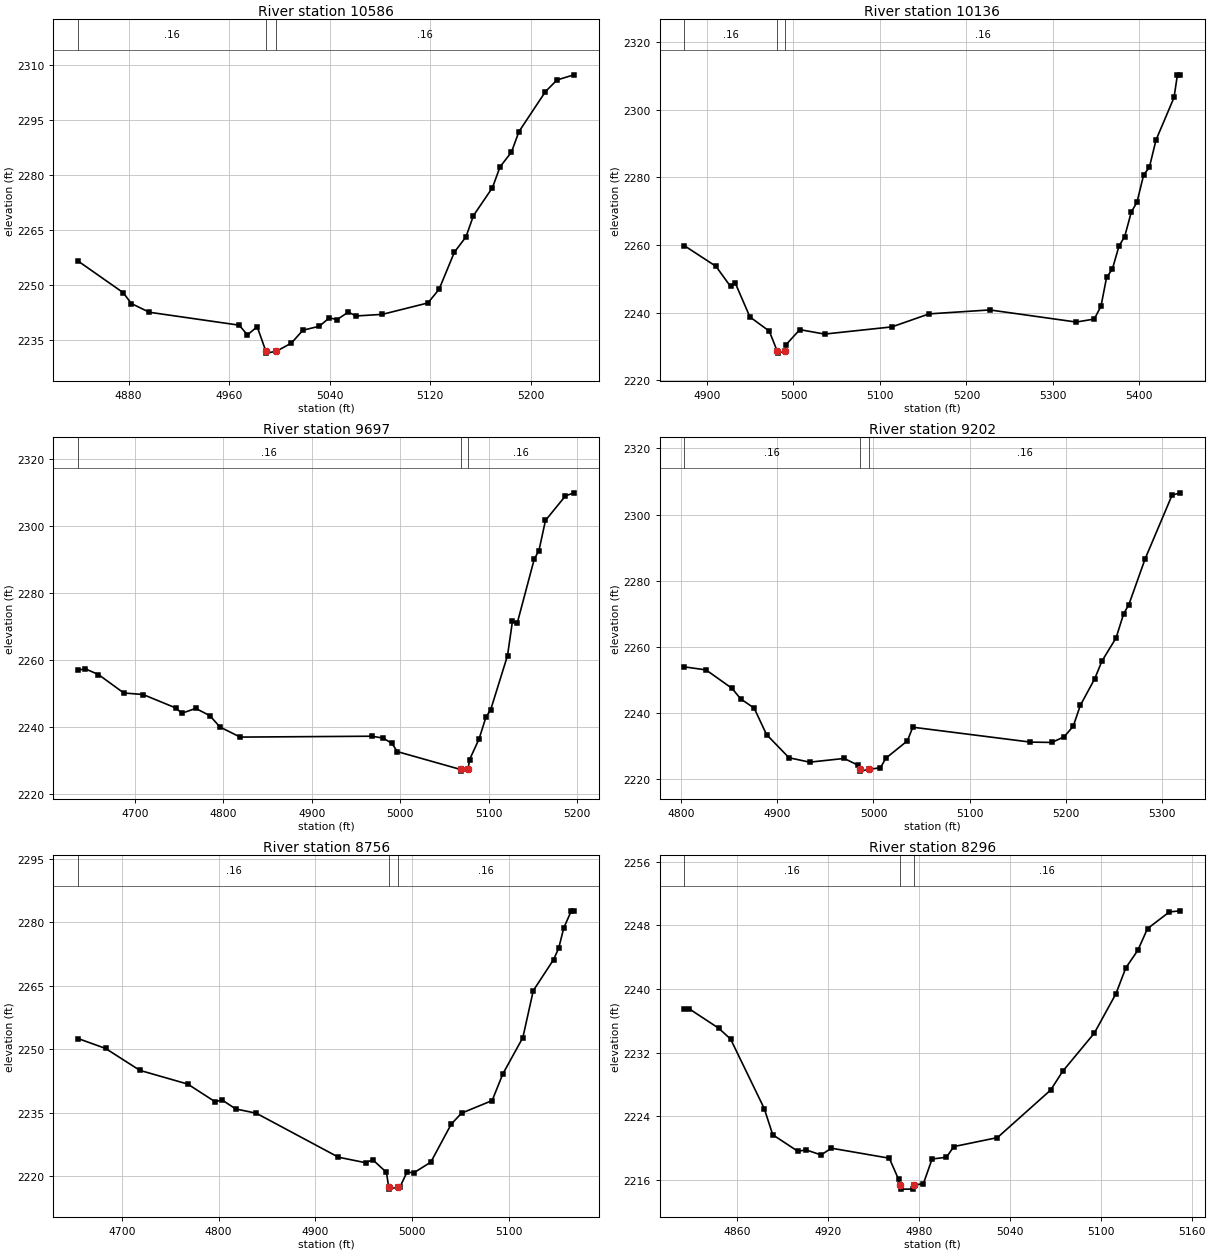
Type RM Length L Ch R = 1,10586,450,450,450
BEGIN DESCRIPTION:
73
END DESCRIPTION:
XS GIS Cut Line= 3
      1500205.02      6787238.02      1500104.22      6787117.65
      1499905.00      6786988.00
#Sta/Elev= 30
  4839.9 2256.46  4875.7 2247.86  4882.2 2244.89  4896.5 2242.51  4968.1 2238.98
  4974.6 2236.32  4982.4 2238.56  4989.3 2231.85  4989.8 2231.35  4997.6 2231.85
  5009.6 2234.08  5018.8 2237.61  5031.8 2238.68  5039.9 2240.99  5045.9 2240.49
  5055.0 2242.56  5061.0 2241.49  5082.1 2241.94  5118.3 2245.05  5127.2 2248.77
  5139.4 2258.92  5148.6 2263.08  5154.6 2268.91  5169.7 2276.53  5175.7 2282.18
  5184.8 2286.22  5190.8 2291.83  5211.9 2302.75  5221.1 2305.93  5234.6 2307.33
#Mann=3,-1,0
  4839.9    0.16       0  4989.3    0.07       0  4997.6    0.16       0
Bank Sta=4989.3,4997.6
Exp/Cntr=0.3,0.1

Type RM Length L Ch R = 1,10136,439,439,439
BEGIN DESCRIPTION:
72
END DESCRIPTION:
XS GIS Cut Line= 3
      1500605.00      6787138.00      1500499.15      6787085.58
      1500204.97      6786737.97
#Sta/Elev= 30
  4873.9 2259.77  4910.3 2253.70  4927.2 2247.73  4932.8 2248.65  4949.6 2238.72
  4972.0 2234.53  4981.3 2228.53  4981.8 2228.03  4989.7 2228.53  4991.5 2230.56
  5007.3 2234.98  5035.9 2233.66  5113.9 2235.79  5156.8 2239.63  5227.1 2240.80
  5327.1 2237.22  5347.9 2238.10  5355.7 2241.90  5362.2 2250.45  5368.8 2252.83
  5376.5 2259.67  5383.1 2262.49  5390.8 2269.76  5397.3 2272.62  5405.1 2280.78
  5411.6 2282.92  5419.4 2291.07  5440.2 2303.61  5444.1 2310.31  5447.4 2310.31
#Mann=3,-1,0
  4873.9    0.16       0  4981.3    0.07       0  4989.7    0.16       0
Bank Sta=4981.3,4989.7
Exp/Cntr=0.3,0.1

Type RM Length L Ch R = 1,9697,495,495,495
BEGIN DESCRIPTION:
71
END DESCRIPTION:
XS GIS Cut Line= 3
      1500805.04      6786888.02      1500468.39      6786701.21
      1500305.00      6786638.00
#Sta/Elev= 30
  4636.1 2256.91  4644.2 2257.28  4659.0 2255.58  4687.6 2250.08  4709.4 2249.62
  4747.1 2245.53  4752.9 2244.00  4768.9 2245.47  4784.8 2243.32  4796.3 2239.92
  4819.1 2236.91  4967.8 2237.17  4980.6 2236.63  4990.7 2235.01  4996.6 2232.58
  5068.1 2227.25  5068.6 2226.75  5076.5 2227.25  5078.4 2230.22  5089.1 2236.39
  5096.9 2242.93  5102.2 2245.09  5121.2 2261.24  5126.8 2271.54  5132.2 2270.95
  5151.4 2290.03  5156.7 2292.59  5164.1 2301.59  5186.7 2308.92  5196.3 2309.83
#Mann=3,-1,0
  4636.1    0.16       0  5068.1    0.07       0  5076.5    0.16       0
Bank Sta=5068.1,5076.5
Exp/Cntr=0.3,0.1

Type RM Length L Ch R = 1,9202,446,446,446
BEGIN DESCRIPTION:
70
END DESCRIPTION:
XS GIS Cut Line= 3
      1501005.02      6786588.02      1500849.39      6786482.39
      1500554.99      6786337.99
#Sta/Elev= 30
  4803.3 2254.00  4825.7 2253.09  4852.8 2247.51  4861.7 2244.35  4875.8 2241.55
  4888.7 2233.55  4912.1 2226.54  4933.6 2225.21  4969.5 2226.33  4984.4 2224.22
  4985.8 2223.00  4986.3 2222.50  4995.2 2223.00  5007.3 2223.54  5012.9 2226.41
  5035.3 2231.65  5040.9 2235.77  5163.4 2231.27  5185.6 2231.17  5198.4 2232.86
  5207.9 2236.07  5215.3 2242.38  5230.2 2250.37  5237.8 2255.77  5252.5 2262.76
  5260.3 2269.99  5265.8 2272.82  5282.8 2286.70  5310.8 2305.91  5319.3 2306.60
#Mann=3,-1,0
  4803.3    0.16       0  4985.8    0.07       0  4995.2    0.16       0
Bank Sta=4985.8,4995.2
Exp/Cntr=0.3,0.1

Type RM Length L Ch R = 1,8756,460,460,460
BEGIN DESCRIPTION:
69
END DESCRIPTION:
XS GIS Cut Line= 3
      1501204.99      6786437.98      1500958.31      6786189.73
      1500804.97      6786137.99
#Sta/Elev= 30
  4655.1 2252.49  4683.3 2250.17  4718.7 2244.98  4768.2 2241.73  4796.5 2237.54
  4803.6 2237.98  4817.7 2235.85  4838.9 2234.84  4923.8 2224.43  4952.0 2223.12
  4959.1 2223.84  4973.3 2220.85  4975.6 2217.38  4976.1 2216.88  4985.0 2217.38
  4987.4 2217.43  4994.5 2220.90  5001.6 2220.75  5019.1 2223.26  5040.2 2232.26
  5050.8 2234.85  5082.4 2237.83  5093.5 2244.16  5114.1 2252.72  5124.9 2263.84
  5145.8 2271.17  5151.1 2273.86  5156.4 2278.70  5164.2 2282.72  5166.9 2282.72
#Mann=3,-1,0
  4655.1    0.16       0  4975.6    0.07       0  4985.0    0.16       0
Bank Sta=4975.6,4985
Exp/Cntr=0.3,0.1

Type RM Length L Ch R = 1,8296,490,490,490
BEGIN DESCRIPTION:
68
END DESCRIPTION:
XS GIS Cut Line= 3
      1501355.01      6786038.01      1501277.55      6785888.12
      1501154.98      6785787.98
#Sta/Elev= 30
  4825.5 2237.55  4828.3 2237.55  4848.0 2235.08  4855.9 2233.71  4878.1 2224.97
  4883.7 2221.67  4900.2 2219.60  4905.8 2219.76  4915.6 2219.13  4922.4 2219.98
  4960.6 2218.72  4966.7 2216.06  4967.5 2215.33  4968.0 2214.83  4976.5 2214.83
  4977.0 2215.33  4983.1 2215.53  4988.8 2218.62  4998.3 2218.84  5003.1 2220.18
  5031.9 2221.31  5067.0 2227.29  5074.9 2229.64  5095.8 2234.45  5110.1 2239.42
  5116.6 2242.67  5124.5 2244.87  5130.9 2247.60  5145.3 2249.70  5152.5 2249.84
#Mann=3,-1,0
  4825.5    0.16       0  4967.5    0.07       0  4977.0    0.16       0
Bank Sta=4967.5,4977
Exp/Cntr=0.3,0.1