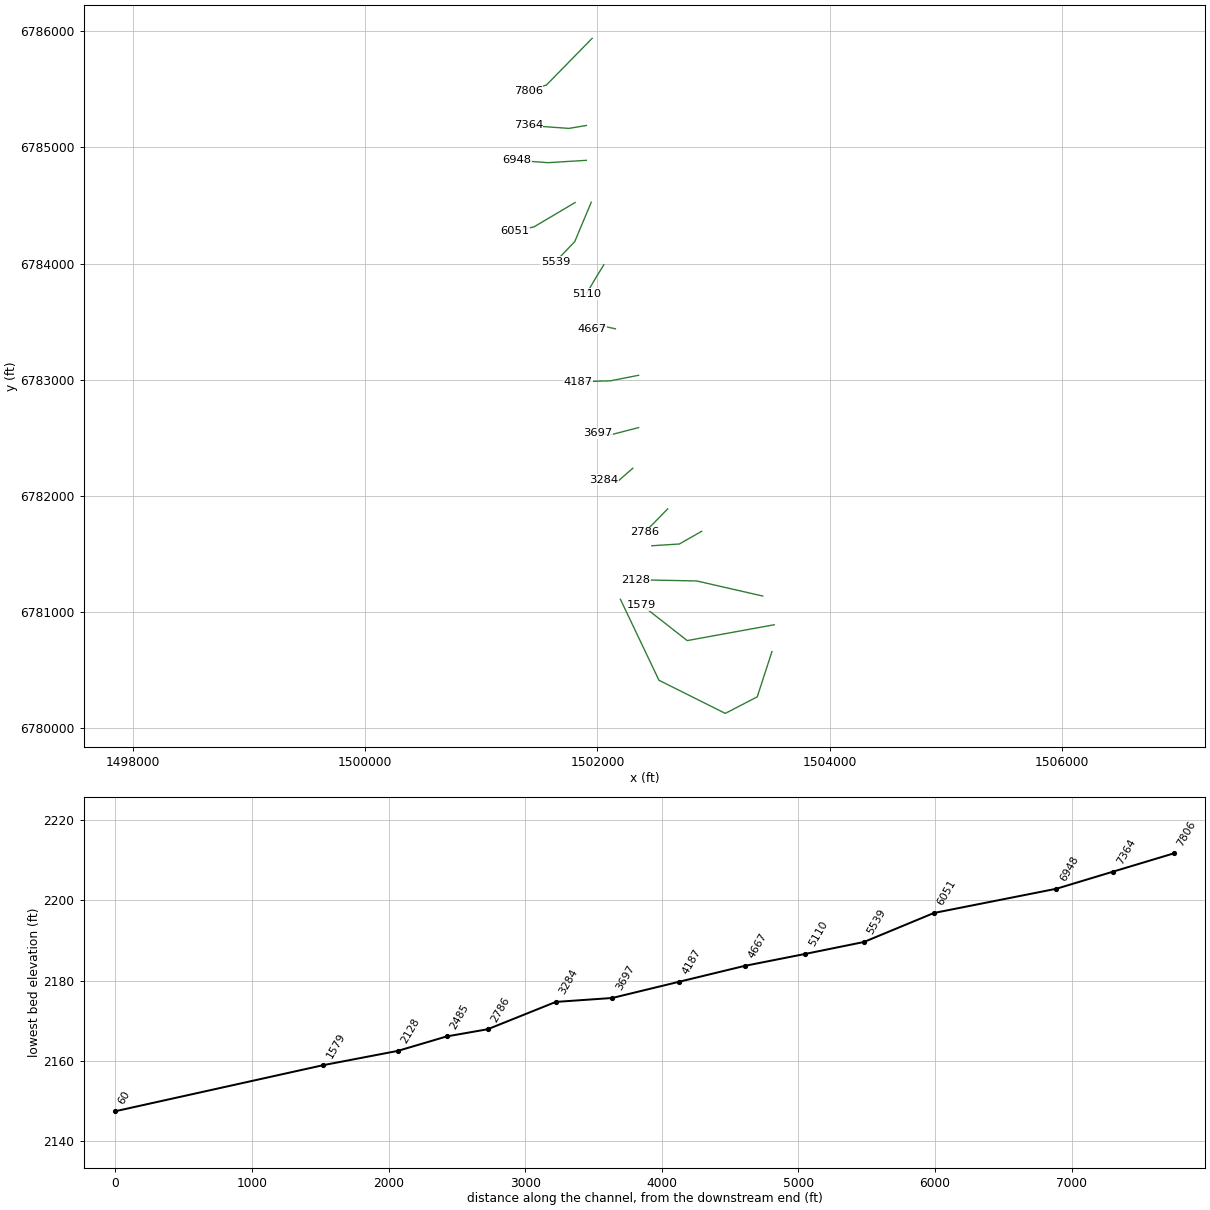
HEC-RAS study Elm 23.prj: Elm 23 Base Level Engineering

--- Elm 23.g01 (geometry) --- (continued)

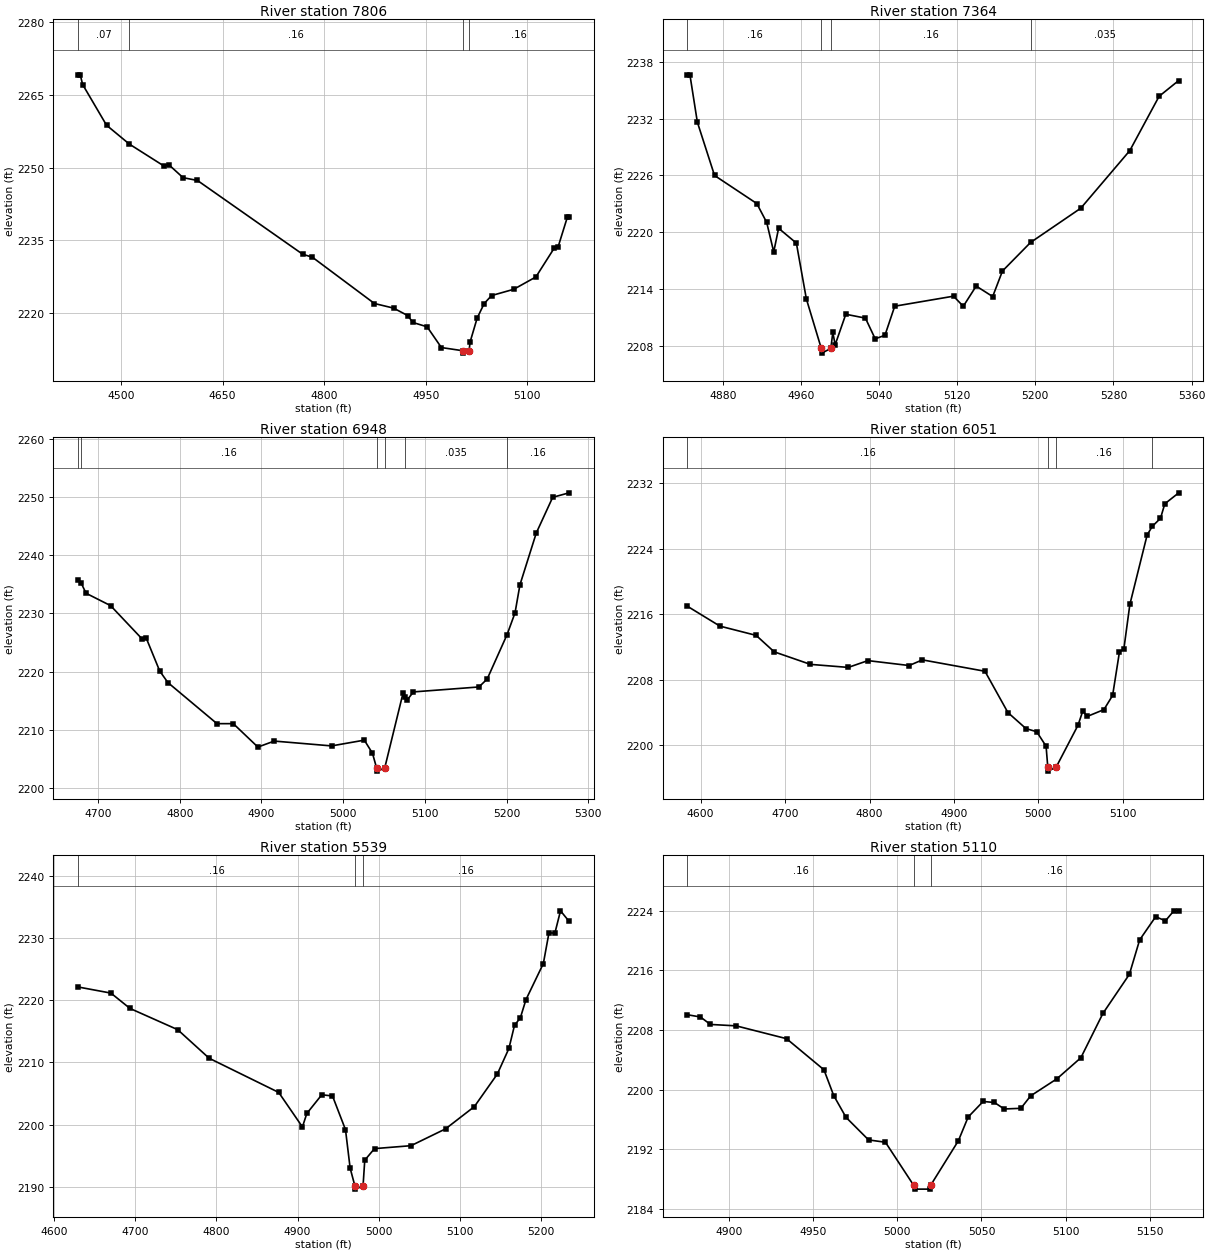
Type RM Length L Ch R = 1,7806,442,442,442
BEGIN DESCRIPTION:
67
END DESCRIPTION:
XS GIS Cut Line= 3
      1501955.02      6785938.02      1501561.08      6785535.80
      1501405.04      6785488.01
#Sta/Elev= 30
  4435.9 2269.16  4439.4 2269.16  4443.0 2267.15  4478.3 2258.76  4512.0 2254.87
  4563.2 2250.34  4570.3 2250.62  4591.4 2247.94  4612.7 2247.36  4768.3 2232.13
  4782.5 2231.53  4874.3 2221.97  4902.6 2221.02  4923.9 2219.45  4930.9 2218.07
  4952.2 2217.16  4973.3 2212.88  5004.7 2212.23  5005.2 2211.73  5014.3 2212.23
  5015.7 2214.01  5026.2 2218.97  5036.6 2221.97  5047.5 2223.61  5080.2 2224.90
  5113.0 2227.45  5140.5 2233.49  5145.8 2233.64  5159.5 2239.78  5162.1 2239.78
#Mann=4,-1,0
  4435.9    0.07       0  4512.0    0.16       0  5004.7    0.07       0
  5014.3    0.16       0
Bank Sta=5004.7,5014.3
Exp/Cntr=0.3,0.1

Type RM Length L Ch R = 1,7364,416,416,416
BEGIN DESCRIPTION:
66
END DESCRIPTION:
XS GIS Cut Line= 3
      1501904.97      6785188.00      1501755.37      6785162.82
      1501404.98      6785188.00
#Sta/Elev= 30
  4843.8 2236.62  4846.3 2236.62  4853.9 2231.62  4871.5 2225.98  4914.8 2223.01
  4924.9 2221.02  4932.1 2217.90  4937.1 2220.40  4955.3 2218.83  4965.5 2212.94
  4980.8 2207.70  4981.3 2207.20  4990.6 2207.70  4992.6 2209.39  4995.0 2208.08
  5005.9 2211.31  5026.0 2210.90  5036.0 2208.71  5046.0 2209.09  5056.0 2212.16
  5116.2 2213.22  5126.2 2212.15  5139.4 2214.29  5156.3 2213.18  5166.3 2215.88
  5195.1 2218.90  5246.5 2222.52  5296.7 2228.61  5326.7 2234.35  5346.8 2236.02
#Mann=4,-1,0
  4843.8    0.16       0  4980.8    0.07       0  4990.6    0.16       0
  5195.1   0.035       0
Bank Sta=4980.8,4990.6
Exp/Cntr=0.3,0.1

Type RM Length L Ch R = 1,6948,897,897,897
BEGIN DESCRIPTION:
65
END DESCRIPTION:
XS GIS Cut Line= 3
      1501904.99      6784888.00      1501574.60      6784867.84
      1501304.95      6784888.00
#Sta/Elev= 30
  4675.2 2235.67  4679.2 2235.23  4685.2 2233.46  4715.3 2231.33  4753.8 2225.62
  4758.8 2225.80  4775.4 2220.11  4785.4 2218.13  4845.5 2211.07  4865.5 2211.07
  4895.6 2207.05  4915.6 2208.08  4985.8 2207.25  5025.9 2208.24  5035.9 2205.98
  5041.0 2203.42  5041.5 2202.92  5050.8 2203.42  5073.2 2216.26  5075.8 2215.66
  5078.2 2215.10  5086.0 2216.52  5166.2 2217.37  5176.3 2218.73  5200.7 2226.37
  5210.4 2230.10  5216.4 2234.90  5236.4 2243.80  5256.5 2249.93  5276.6 2250.70
#Mann=6,-1,0
  4675.2    0.07       0  4679.2    0.16       0  5041.0    0.07       0
  5050.8    0.16       0  5075.8   0.035       0  5200.7    0.16       0
Bank Sta=5041,5050.8
Exp/Cntr=0.3,0.1

Type RM Length L Ch R = 1,6051,512,512,512
BEGIN DESCRIPTION:
64
END DESCRIPTION:
XS GIS Cut Line= 3
      1501808.82      6784525.09      1501455.34      6784315.60
      1501288.53      6784278.39
#Sta/Elev= 30
  4584.4 2216.99  4622.8 2214.57  4665.7 2213.44  4687.1 2211.43  4730.0 2209.90
  4774.8 2209.53  4798.1 2210.36  4846.9 2209.76  4862.6 2210.45  4936.7 2209.06
  4963.9 2204.02  4985.3 2202.06  4998.0 2201.68  5009.1 2199.91  5011.1 2197.37
  5011.6 2196.87  5021.1 2197.37  5046.9 2202.47  5052.6 2204.22  5057.7 2203.54
  5077.6 2204.38  5087.9 2206.11  5096.0 2211.43  5101.2 2211.77  5108.3 2217.21
  5128.8 2225.70  5134.9 2226.75  5144.6 2227.73  5149.7 2229.50  5166.2 2230.84
#Mann=4,-1,0
  4584.4    0.16       0  5011.1    0.07       0  5021.1    0.16       0
  5134.9    0.07       0
Bank Sta=5011.1,5021.1
Exp/Cntr=0.3,0.1

Type RM Length L Ch R = 1,5539,429,429,429
BEGIN DESCRIPTION:
63
END DESCRIPTION:
XS GIS Cut Line= 3
      1501947.17      6784527.08      1501804.92      6784187.66
      1501640.86      6784017.22
#Sta/Elev= 30
  4629.6 2222.13  4670.3 2221.14  4693.7 2218.68  4752.5 2215.26  4791.2 2210.67
  4876.8 2205.18  4906.0 2199.63  4911.4 2201.80  4929.8 2204.80  4943.0 2204.61
  4959.0 2199.19  4964.7 2193.02  4970.6 2190.14  4971.1 2189.64  4980.6 2190.14
  4982.7 2194.29  4994.7 2196.15  5039.6 2196.62  5082.1 2199.32  5117.6 2202.90
  5145.9 2208.14  5160.1 2212.24  5167.0 2215.96  5174.2 2217.17  5181.1 2220.09
  5202.5 2225.89  5209.4 2230.82  5216.7 2230.78  5223.6 2234.36  5234.2 2232.67
#Mann=3,-1,0
  4629.6    0.16       0  4970.6    0.07       0  4980.6    0.16       0
Bank Sta=4970.6,4980.6
Exp/Cntr=0.3,0.1

Type RM Length L Ch R = 1,5110,443,443,443
BEGIN DESCRIPTION:
62
END DESCRIPTION:
XS GIS Cut Line= 3
      1502055.00      6783988.00      1501996.84      6783894.05
      1501904.98      6783737.97
#Sta/Elev= 30
  4875.5 2210.06  4883.2 2209.76  4889.1 2208.76  4904.4 2208.57  4934.3 2206.85
  4956.5 2202.68  4962.3 2199.22  4969.6 2196.30  4983.0 2193.27  4993.0 2192.96
  5009.8 2187.17  5010.3 2186.67  5019.3 2186.67  5019.8 2187.17  5036.3 2193.16
  5042.1 2196.34  5051.0 2198.43  5057.7 2198.29  5063.5 2197.42  5073.4 2197.51
  5079.2 2199.18  5094.8 2201.47  5109.0 2204.29  5122.1 2210.24  5137.8 2215.48
  5143.9 2220.10  5153.4 2223.21  5159.2 2222.66  5164.2 2224.00  5167.1 2224.00
#Mann=3,-1,0
  4875.5    0.16       0  5009.8    0.07       0  5019.8    0.16       0
Bank Sta=5009.8,5019.8
Exp/Cntr=0.3,0.1

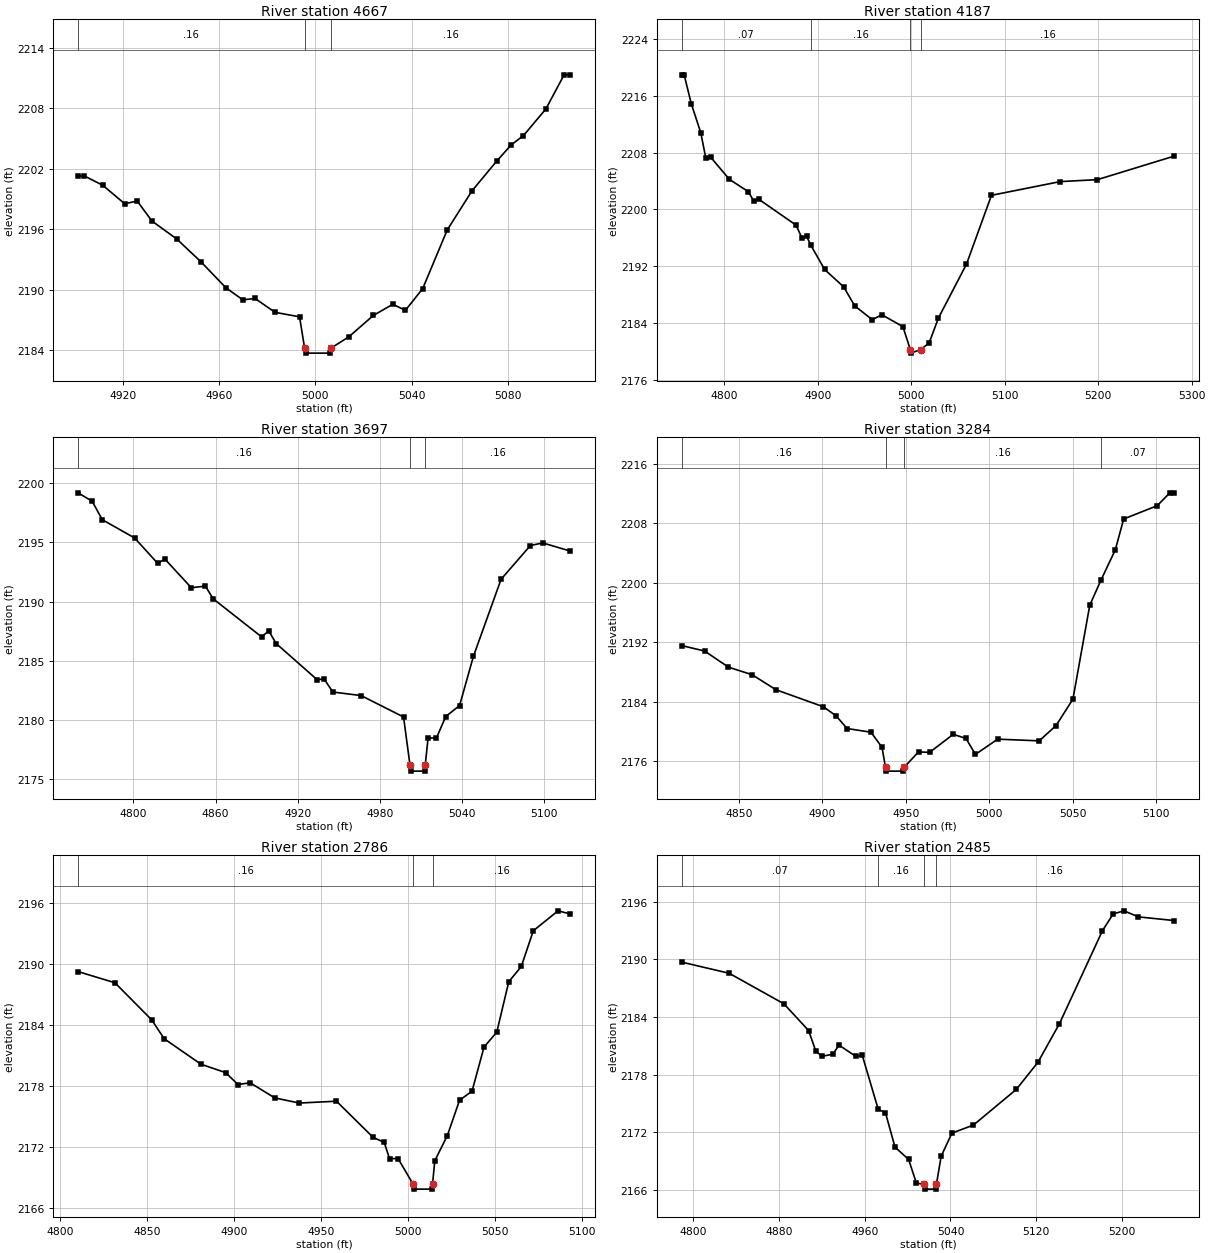
Type RM Length L Ch R = 1,4667,480,480,480
BEGIN DESCRIPTION:
61
END DESCRIPTION:
XS GIS Cut Line= 3
      1502155.02      6783438.00      1502055.17      6783459.74
      1501954.99      6783438.00
#Sta/Elev= 30
  4901.3 2201.27  4903.9 2201.27  4911.6 2200.34  4920.7 2198.51  4925.9 2198.78
  4932.0 2196.80  4942.3 2195.02  4952.5 2192.73  4962.7 2190.19  4969.8 2188.98
  4974.9 2189.11  4983.2 2187.74  4993.4 2187.29  4995.5 2184.19  4996.0 2183.69
  5006.0 2183.69  5006.5 2184.19  5013.9 2185.31  5024.1 2187.43  5032.2 2188.54
  5037.4 2187.93  5044.6 2190.09  5054.8 2195.91  5065.1 2199.79  5075.3 2202.72
  5081.4 2204.35  5086.5 2205.27  5095.8 2207.91  5103.4 2211.30  5106.0 2211.30
#Mann=3,-1,0
  4901.3    0.16       0  4995.5    0.07       0  5006.5    0.16       0
Bank Sta=4995.5,5006.5
Exp/Cntr=0.3,0.1

Type RM Length L Ch R = 1,4187,490,490,490
BEGIN DESCRIPTION:
60
END DESCRIPTION:
XS GIS Cut Line= 4
      1502355.04      6783038.01      1502109.19      6782989.73
      1502026.75      6782988.36      1501833.12      6782980.21
#Sta/Elev= 30
  4754.4 2218.95  4757.0 2218.95  4764.6 2214.89  4774.8 2210.78  4780.2 2207.19
  4785.3 2207.35  4805.4 2204.22  4825.8 2202.47  4831.6 2201.12  4836.7 2201.43
  4876.7 2197.77  4883.0 2195.96  4888.1 2196.18  4892.5 2194.94  4907.3 2191.52
  4927.7 2189.06  4939.5 2186.39  4958.3 2184.44  4968.5 2185.14  4991.0 2183.47
  4999.0 2180.23  4999.5 2179.73  5010.1 2180.23  5019.1 2181.16  5029.1 2184.69
  5059.1 2192.27  5085.8 2201.97  5159.2 2203.90  5199.2 2204.18  5281.2 2207.49
#Mann=4,-1,0
  4754.4    0.07       0  4892.5    0.16       0  4999.0    0.07       0
  5010.1    0.16       0
Bank Sta=4999,5010.1
Exp/Cntr=0.3,0.1

Type RM Length L Ch R = 1,3697,413,413,413
BEGIN DESCRIPTION:
59
END DESCRIPTION:
XS GIS Cut Line= 3
      1502355.00      6782588.00      1502104.57      6782522.82
      1502005.00      6782538.00
#Sta/Elev= 30
  4759.6 2199.18  4769.9 2198.47  4777.3 2196.91  4800.9 2195.37  4817.8 2193.22
  4823.0 2193.59  4842.3 2191.17  4852.6 2191.30  4858.3 2190.23  4893.7 2187.01
  4898.8 2187.53  4904.3 2186.45  4934.2 2183.40  4939.3 2183.47  4945.6 2182.36
  4966.3 2182.06  4997.3 2180.25  5002.0 2176.18  5002.5 2175.68  5012.6 2175.68
  5013.1 2176.18  5015.2 2178.48  5021.3 2178.48  5028.1 2180.29  5038.2 2181.22
  5048.3 2185.37  5068.5 2191.88  5089.9 2194.73  5098.9 2194.95  5119.1 2194.26
#Mann=3,-1,0
  4759.6    0.16       0  5002.0    0.07       0  5013.1    0.16       0
Bank Sta=5002,5013.1
Exp/Cntr=0.3,0.1

Type RM Length L Ch R = 1,3284,498,498,498
BEGIN DESCRIPTION:
58
END DESCRIPTION:
XS GIS Cut Line= 3
      1502304.96      6782237.97      1502171.46      6782121.25
      1502054.99      6782138.00
#Sta/Elev= 30
  4815.7 2191.58  4829.4 2190.85  4843.7 2188.68  4857.9 2187.66  4872.1 2185.65
  4900.6 2183.35  4908.2 2182.13  4914.8 2180.43  4929.1 2179.93  4935.7 2177.90
  4937.8 2175.20  4938.3 2174.70  4948.4 2174.70  4948.9 2175.20  4957.6 2177.29
  4964.2 2177.22  4978.4 2179.65  4986.0 2179.09  4991.7 2176.95  5005.0 2179.00
  5029.9 2178.77  5040.0 2180.83  5050.1 2184.38  5060.2 2197.02  5066.9 2200.38
  5075.5 2204.46  5080.5 2208.60  5100.6 2210.39  5108.2 2212.12  5110.7 2212.12
#Mann=4,-1,0
  4815.7    0.16       0  4937.8    0.07       0  4948.9    0.16       0
  5066.9    0.07       0
Bank Sta=4937.8,4948.9
Exp/Cntr=0.3,0.1

Type RM Length L Ch R = 1,2786,301,301,301
BEGIN DESCRIPTION:
57
END DESCRIPTION:
XS GIS Cut Line= 3
      1502604.98      6781887.98      1502481.29      6781761.14
      1502404.97      6781687.97
#Sta/Elev= 30
  4810.2 2189.27  4831.4 2188.17  4852.5 2184.53  4859.7 2182.67  4880.8 2180.17
  4895.0 2179.34  4902.1 2178.17  4909.1 2178.34  4923.3 2176.85  4937.4 2176.35
  4958.7 2176.53  4979.8 2172.97  4986.1 2172.49  4989.2 2170.89  4994.1 2170.89
  5002.7 2168.39  5003.2 2167.89  5013.4 2167.89  5013.9 2168.39  5015.2 2170.68
  5022.4 2173.15  5029.4 2176.62  5036.6 2177.52  5043.5 2181.86  5050.8 2183.31
  5057.7 2188.27  5064.9 2189.77  5071.8 2193.28  5086.0 2195.24  5093.1 2194.93
#Mann=3,-1,0
  4810.2    0.16       0  5002.7    0.07       0  5013.9    0.16       0
Bank Sta=5002.7,5013.9
Exp/Cntr=0.3,0.1

Type RM Length L Ch R = 1,2485,357,357,357
BEGIN DESCRIPTION:
56
END DESCRIPTION:
XS GIS Cut Line= 3
      1502897.76      6781695.21      1502705.41      6781585.88
      1502468.44      6781570.79
#Sta/Elev= 30
  4789.6 2189.72  4833.8 2188.56  4884.8 2185.38  4907.8 2182.60  4914.5 2180.46
  4920.3 2179.92  4930.4 2180.13  4936.1 2181.08  4952.0 2179.90  4957.8 2180.02
  4972.7 2174.39  4979.4 2174.05  4988.3 2170.46  5001.0 2169.18  5008.2 2166.72
  5015.7 2166.59  5016.2 2166.09  5026.4 2166.09  5026.9 2166.59  5031.3 2169.51
  5041.3 2171.92  5061.4 2172.76  5101.4 2176.48  5121.5 2179.30  5141.5 2183.31
  5181.6 2193.00  5191.6 2194.74  5201.6 2195.06  5215.1 2194.43  5248.3 2194.05
#Mann=4,-1,0
  4789.6    0.07       0  4972.7    0.16       0  5015.7    0.07       0
  5026.9    0.16       0
Bank Sta=5015.7,5026.9
Exp/Cntr=0.3,0.1

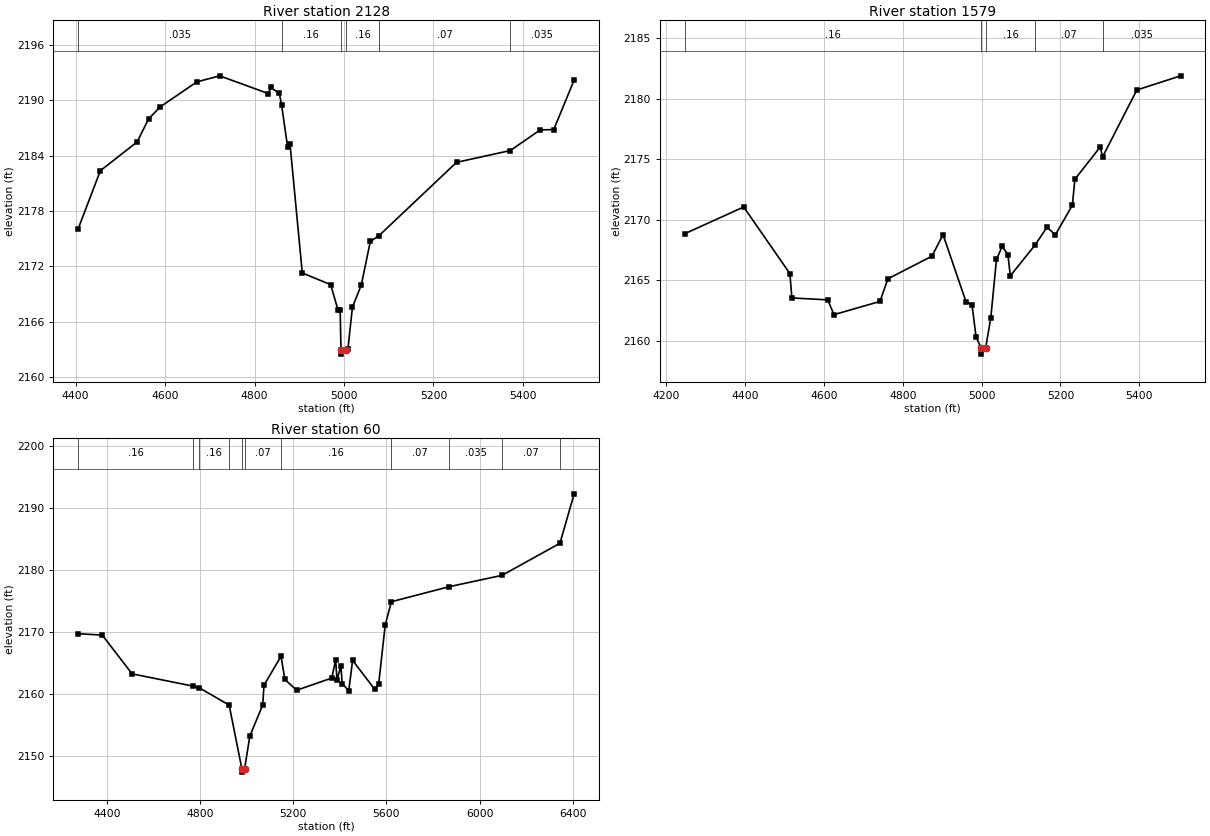
Type RM Length L Ch R = 1,2128,549,549,549
BEGIN DESCRIPTION:
769
END DESCRIPTION:
XS GIS Cut Line= 3
      1503423.39      6781137.90      1502854.76      6781267.90
      1502329.26      6781278.20
#Sta/Elev= 30
  4405.7 2176.09  4455.3 2182.38  4537.4 2185.49  4563.1 2188.00  4588.7 2189.28
  4670.8 2192.00  4722.0 2192.66  4831.1 2190.73  4836.2 2191.40  4855.4 2190.75
  4860.5 2189.49  4874.0 2184.91  4879.2 2185.32  4906.7 2171.29  4970.2 2170.02
  4986.3 2167.32  4991.4 2167.32  4993.2 2162.99  4993.7 2162.49  5004.4 2162.99
  5008.8 2163.05  5018.8 2167.57  5038.8 2170.01  5058.8 2174.70  5078.6 2175.35
  5251.6 2183.28  5371.8 2184.56  5438.8 2186.80  5468.9 2186.83  5514.6 2192.20
#Mann=6,-1,0
  4405.7   0.035       0  4860.5    0.16       0  4993.2    0.07       0
  5004.4    0.16       0  5078.6    0.07       0  5371.8   0.035       0
Bank Sta=4993.2,5004.4
Exp/Cntr=0.3,0.1

Type RM Length L Ch R = 1,1579,1519,1519,1519
BEGIN DESCRIPTION:
768
END DESCRIPTION:
XS GIS Cut Line= 3
      1503522.24      6780890.88      1502773.22      6780754.52
      1502381.90      6781060.86
#Sta/Elev= 30
  4246.7 2168.85  4396.4 2171.06  4513.6 2165.56  4518.7 2163.55  4609.8 2163.39
  4625.4 2162.17  4742.2 2163.26  4762.3 2165.13  4874.1 2167.00  4902.2 2168.78
  4960.6 2163.22  4975.7 2163.00  4985.9 2160.35  4999.0 2159.41  4999.5 2158.91
  5010.2 2159.41  5023.3 2161.88  5037.8 2166.73  5052.2 2167.80  5066.7 2167.13
  5073.0 2165.38  5136.0 2167.93  5166.2 2169.40  5187.0 2168.75  5230.4 2171.21
  5236.7 2173.35  5300.9 2176.01  5307.2 2175.21  5394.0 2180.72  5505.0 2181.89
#Mann=5,-1,0
  4246.7    0.16       0  4999.0    0.07       0  5010.2    0.16       0
  5136.0    0.07       0  5307.2   0.035       0
Bank Sta=4999,5010.2
Exp/Cntr=0.3,0.1

Type RM Length L Ch R = 1,60,0,0,0
BEGIN DESCRIPTION:
55
END DESCRIPTION:
XS GIS Cut Line= 5
      1503502.45      6780659.70      1503375.96      6780270.35
      1503101.27      6780128.06      1502530.00      6780413.00
      1502198.15      6781110.23
#Sta/Elev= 30
  4276.8 2169.75  4380.2 2169.52  4508.0 2163.28  4768.5 2161.31  4796.1 2161.04
  4924.9 2158.24  4979.6 2147.94  4980.1 2147.44  4990.9 2147.94  5013.7 2153.25
  5068.9 2158.26  5074.5 2161.45  5147.6 2166.11  5164.0 2162.37  5214.9 2160.64
  5365.4 2162.60  5382.2 2165.52  5387.8 2162.29  5404.6 2164.55  5410.2 2161.70
  5438.4 2160.56  5454.9 2165.45  5550.1 2160.77  5566.8 2161.65  5594.8 2171.13
  5621.2 2174.90  5869.2 2177.32  6096.8 2179.16  6345.1 2184.32  6406.1 2192.29
#Mann=11,-1,0
  4276.8    0.16       0  4768.5    0.07       0  4796.1    0.16       0
  4924.9    0.07       0  4979.6    0.07       0  4990.9    0.07       0
  5147.6    0.16       0  5621.2    0.07       0  5869.2   0.035       0
  6096.8    0.07       0  6345.1    0.16       0
Bank Sta=4979.6,4990.9
Exp/Cntr=0.3,0.1

Chan Stop Cuts=-1