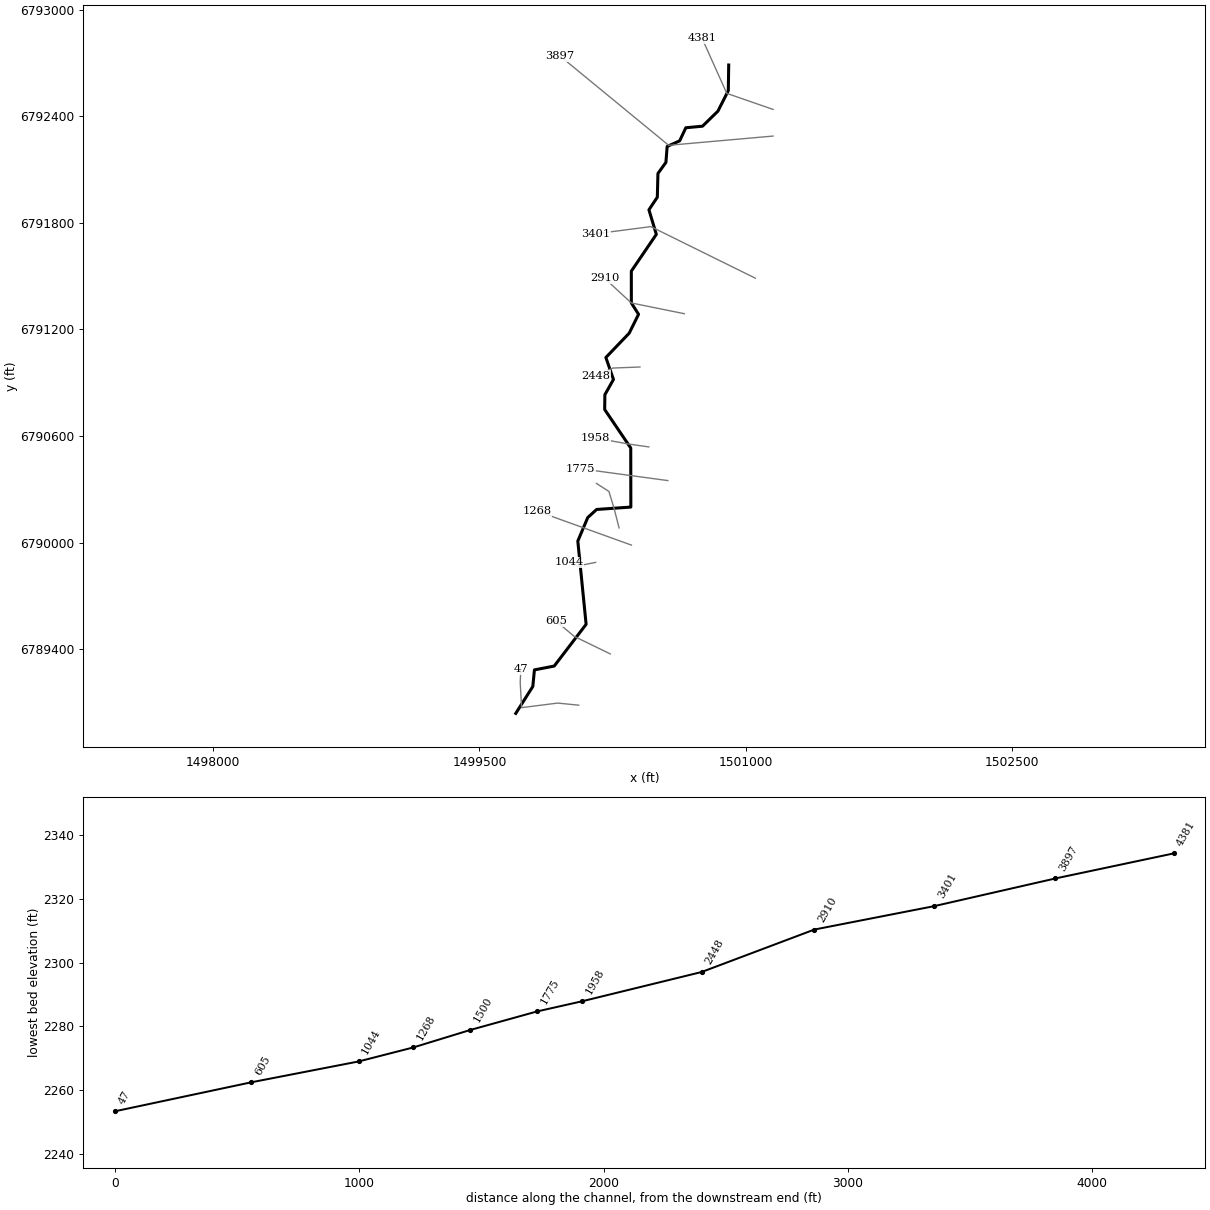
--- Elm 24.prj (project) ---

Proj Title=Elm 24 Base Level Engineering
Current Plan=p01
Default Exp/Contr=0.3,0.1
English Units
Geom File=g01
Flow File=f01
Plan File=p01
BEGIN DESCRIPTION:
Elm 24
END DESCRIPTION:

--- Elm 24.p01 (plan) ---

Plan Title=Multiple Run
Short Identifier=Multiple
Geom File=g01
Flow File=f01
Subcritical Flow
K Sum by GR= 0
Std Step Tol= 0.01
Critical Tol= 0.01
Num of Std Step Trials= 20
Max Error Tol= 0.3
Flow Tol Ratio= 0.001
Split Flow NTrial= 30
Split Flow Tol= 0.02
Split Flow Ratio= 0.02
Log Output Level= 0
Friction Slope Method= 1
Unsteady Friction Slope Method= 2
Unsteady Bridges Friction Slope Method= 1
Parabolic Critical Depth
Global Vel Dist=  1 , 1 , 1
Global Log Level= 0
CheckData=True
Encroach Param= -1, 0, 0, 0
BEGIN DESCRIPTION:
Multiple Run
END DESCRIPTION:

--- Elm 24.f01 (steady flow) ---

Flow Title=Multiple
Number of Profiles=7
Profile Names=10-year,25-year,50-year,1pct_min,100-year,1pct_plu,500-year
River Rch & RM= Elm 24,Reach-1,4381
     259     364     453     350     560     771     866
Boundary for River Rch & Prof#=Elm 24,Reach-1,1
Up Type=0
Dn Type=3
Dn Slope=0.005
Boundary for River Rch & Prof#=Elm 24,Reach-1,2
Up Type=0
Dn Type=3
Dn Slope=0.005
Boundary for River Rch & Prof#=Elm 24,Reach-1,3
Up Type=0
Dn Type=3
Dn Slope=0.005
Boundary for River Rch & Prof#=Elm 24,Reach-1,4
Up Type=0
Dn Type=3
Dn Slope=0.005
Boundary for River Rch & Prof#=Elm 24,Reach-1,5
Up Type=0
Dn Type=3
Dn Slope=0.005
Boundary for River Rch & Prof#=Elm 24,Reach-1,6
Up Type=0
Dn Type=3
Dn Slope=0.005
Boundary for River Rch & Prof#=Elm 24,Reach-1,7
Up Type=0
Dn Type=3
Dn Slope=0.005

--- Elm 24.g01 (geometry) ---

Geom Title=Existing Conditions

River Reach=Elm 24,Reach-1
Reach XY= 30
      1500905.00      6792688.00      1500902.81      6792543.91
      1500844.25      6792428.29      1500757.38      6792343.54
      1500663.35      6792334.81      1500628.63      6792261.06
      1500558.19      6792229.65      1500551.11      6792139.67
      1500506.23      6792077.49      1500502.73      6791943.94
      1500455.39      6791872.72      1500497.19      6791734.59
      1500356.20      6791527.50      1500356.38      6791348.44
      1500396.96      6791284.68      1500344.25      6791178.32
      1500212.80      6791041.42      1500255.58      6790917.96
      1500207.17      6790832.03      1500206.08      6790748.54
      1500352.94      6790532.14      1500353.52      6790199.48
      1500160.67      6790186.02      1500110.71      6790140.59
      1500054.64      6790008.15      1500101.45      6789539.47
      1499921.76      6789304.46      1499810.11      6789282.89
      1499801.15      6789189.66      1499705.00      6789038.00

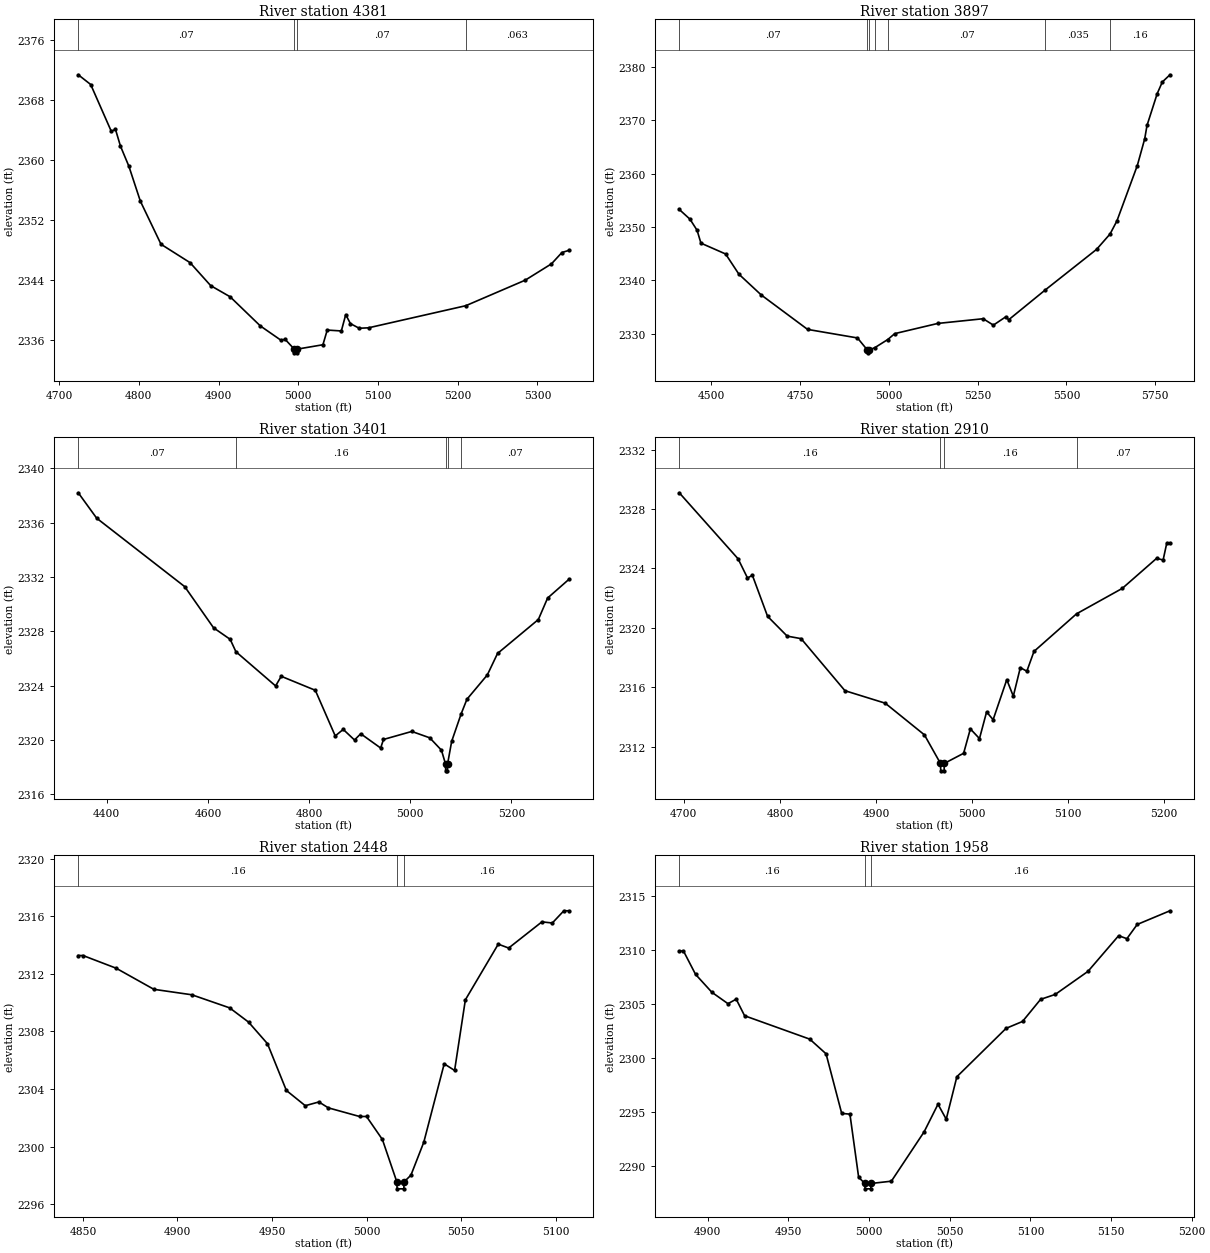
Type RM Length L Ch R = 1,4381,484,484,484
BEGIN DESCRIPTION:
423
END DESCRIPTION:
XS GIS Cut Line= 3
      1501155.01      6792438.00      1500894.21      6792528.33
      1500755.01      6792837.98
#Sta/Elev= 30
  4724.0 2371.38  4739.6 2370.08  4765.4 2363.84  4770.7 2364.09  4776.9 2361.87
  4787.5 2359.17  4801.9 2354.51  4827.8 2348.76  4864.2 2346.31  4890.1 2343.24
  4914.5 2341.75  4952.4 2337.86  4978.0 2335.97  4983.5 2336.07  4994.9 2334.77
  4995.2 2334.27  4998.7 2334.27  4998.9 2334.77  5030.9 2335.35  5036.3 2337.31
  5054.0 2337.19  5059.5 2339.37  5065.4 2338.17  5076.4 2337.55  5088.1 2337.61
  5210.1 2340.56  5284.7 2343.97  5317.6 2346.15  5330.7 2347.66  5339.5 2347.95
#Mann=4,-1,0
  4724.0    0.07       0  4994.9    0.07       0  4998.9    0.07       0
  5210.1   0.063       0
Bank Sta=4994.9,4998.9
Exp/Cntr=0.3,0.1

Type RM Length L Ch R = 1,3897,496,496,496
BEGIN DESCRIPTION:
422
END DESCRIPTION:
XS GIS Cut Line= 3
      1501154.99      6792288.00      1500566.78      6792235.98
      1499954.99      6792738.01
#Sta/Elev= 30
  4409.5 2353.28  4439.6 2351.46  4459.7 2349.38  4470.5 2346.97  4540.0 2344.94
  4577.5 2341.15  4640.4 2337.26  4770.9 2330.81  4911.4 2329.21  4939.6 2326.92
  4939.8 2326.42  4943.6 2326.92  4960.7 2327.41  4996.6 2328.91  5016.4 2330.02
  5137.7 2331.93  5265.4 2332.81  5294.1 2331.61  5329.3 2333.18  5337.1 2332.61
  5440.2 2338.20  5584.7 2345.80  5622.7 2348.68  5642.1 2351.14  5699.5 2361.51
  5720.3 2366.51  5726.8 2369.02  5755.5 2374.98  5769.9 2377.16  5791.4 2378.51
#Mann=7,-1,0
  4409.5    0.07       0  4939.6    0.07       0  4943.6    0.07       0
  4960.7    0.16       0  4996.6    0.07       0  5440.2   0.035       0
  5622.7    0.16       0
Bank Sta=4939.6,4943.6
Exp/Cntr=0.3,0.1

Type RM Length L Ch R = 1,3401,491,491,491
BEGIN DESCRIPTION:
421
END DESCRIPTION:
XS GIS Cut Line= 3
      1501054.96      6791488.02      1500466.19      6791778.21
      1500154.98      6791738.00
#Sta/Elev= 30
  4343.6 2338.21  4380.0 2336.34  4554.1 2331.30  4611.1 2328.27  4644.0 2327.42
  4655.3 2326.51  4733.8 2323.99  4744.9 2324.70  4812.3 2323.67  4851.7 2320.31
  4867.5 2320.79  4889.8 2320.01  4902.1 2320.47  4941.5 2319.42  4947.1 2320.05
  5003.1 2320.64  5038.6 2320.17  5061.7 2319.26  5069.8 2318.24  5070.0 2317.74
  5073.5 2317.74  5073.8 2318.24  5081.9 2319.91  5100.7 2321.94  5112.1 2323.01
  5152.4 2324.80  5172.6 2326.38  5253.3 2328.88  5271.6 2330.46  5313.8 2331.84
#Mann=5,-1,0
  4343.6    0.07       0  4655.3    0.16       0  5069.8    0.07       0
  5073.8    0.16       0  5100.7    0.07       0
Bank Sta=5069.8,5073.8
Exp/Cntr=0.3,0.1

Type RM Length L Ch R = 1,2910,462,462,462
BEGIN DESCRIPTION:
420
END DESCRIPTION:
XS GIS Cut Line= 3
      1500655.03      6791287.99      1500356.38      6791348.44
      1500205.00      6791488.00
#Sta/Elev= 30
  4695.3 2329.09  4756.5 2324.65  4766.3 2323.36  4771.4 2323.54  4787.2 2320.78
  4807.6 2319.45  4822.1 2319.28  4867.7 2315.78  4909.6 2314.94  4950.4 2312.81
  4967.1 2310.89  4967.4 2310.39  4970.9 2310.39  4971.1 2310.89  4991.2 2311.57
  4998.2 2313.21  5007.7 2312.56  5015.1 2314.35  5021.9 2313.83  5036.1 2316.52
  5042.9 2315.41  5050.2 2317.33  5057.0 2317.09  5064.4 2318.42  5108.7 2320.95
  5156.3 2322.66  5192.0 2324.68  5198.8 2324.57  5202.5 2325.68  5205.9 2325.68
#Mann=4,-1,0
  4695.3    0.16       0  4967.1    0.07       0  4971.1    0.16       0
  5108.7    0.07       0
Bank Sta=4967.1,4971.1
Exp/Cntr=0.3,0.1

Type RM Length L Ch R = 1,2448,490,490,490
BEGIN DESCRIPTION:
419
END DESCRIPTION:
XS GIS Cut Line= 3
      1500405.01      6790988.00      1500252.63      6790982.11
      1500155.03      6790938.01
#Sta/Elev= 30
  4847.5 2313.28  4850.0 2313.28  4867.5 2312.40  4887.5 2310.93  4907.6 2310.55
  4927.6 2309.64  4937.6 2308.65  4947.6 2307.15  4957.6 2303.90  4967.6 2302.84
  4974.8 2303.10  4979.8 2302.69  4996.3 2302.09  5000.0 2302.09  5008.4 2300.49
  5016.0 2297.56  5016.2 2297.06  5019.7 2297.06  5020.0 2297.56  5023.5 2298.01
  5030.3 2300.30  5041.1 2305.75  5046.6 2305.29  5052.3 2310.20  5069.7 2314.07
  5075.2 2313.80  5092.8 2315.62  5098.3 2315.54  5104.4 2316.39  5107.1 2316.39
#Mann=3,-1,0
  4847.5    0.16       0  5016.0    0.07       0  5020.0    0.16       0
Bank Sta=5016,5020
Exp/Cntr=0.3,0.1

Type RM Length L Ch R = 1,1958,183,183,183
BEGIN DESCRIPTION:
418
END DESCRIPTION:
XS GIS Cut Line= 3
      1500455.04      6790537.99      1500338.54      6790554.75
      1500155.02      6790588.00
#Sta/Elev= 30
  4882.3 2309.94  4884.9 2309.94  4892.4 2307.77  4902.5 2306.11  4912.5 2305.05
  4917.6 2305.47  4922.8 2303.93  4963.2 2301.76  4973.3 2300.40  4983.0 2294.87
  4988.1 2294.80  4993.5 2288.95  4997.3 2288.37  4997.5 2287.87  5001.0 2287.87
  5001.3 2288.37  5013.8 2288.58  5034.1 2293.16  5042.7 2295.72  5047.8 2294.33
  5054.4 2298.27  5084.9 2302.76  5095.1 2303.40  5106.3 2305.45  5115.4 2305.91
  5135.7 2308.05  5154.7 2311.36  5159.8 2311.08  5166.2 2312.40  5186.5 2313.67
#Mann=3,-1,0
  4882.3    0.16       0  4997.3    0.07       0  5001.3    0.16       0
Bank Sta=4997.3,5001.3
Exp/Cntr=0.3,0.1

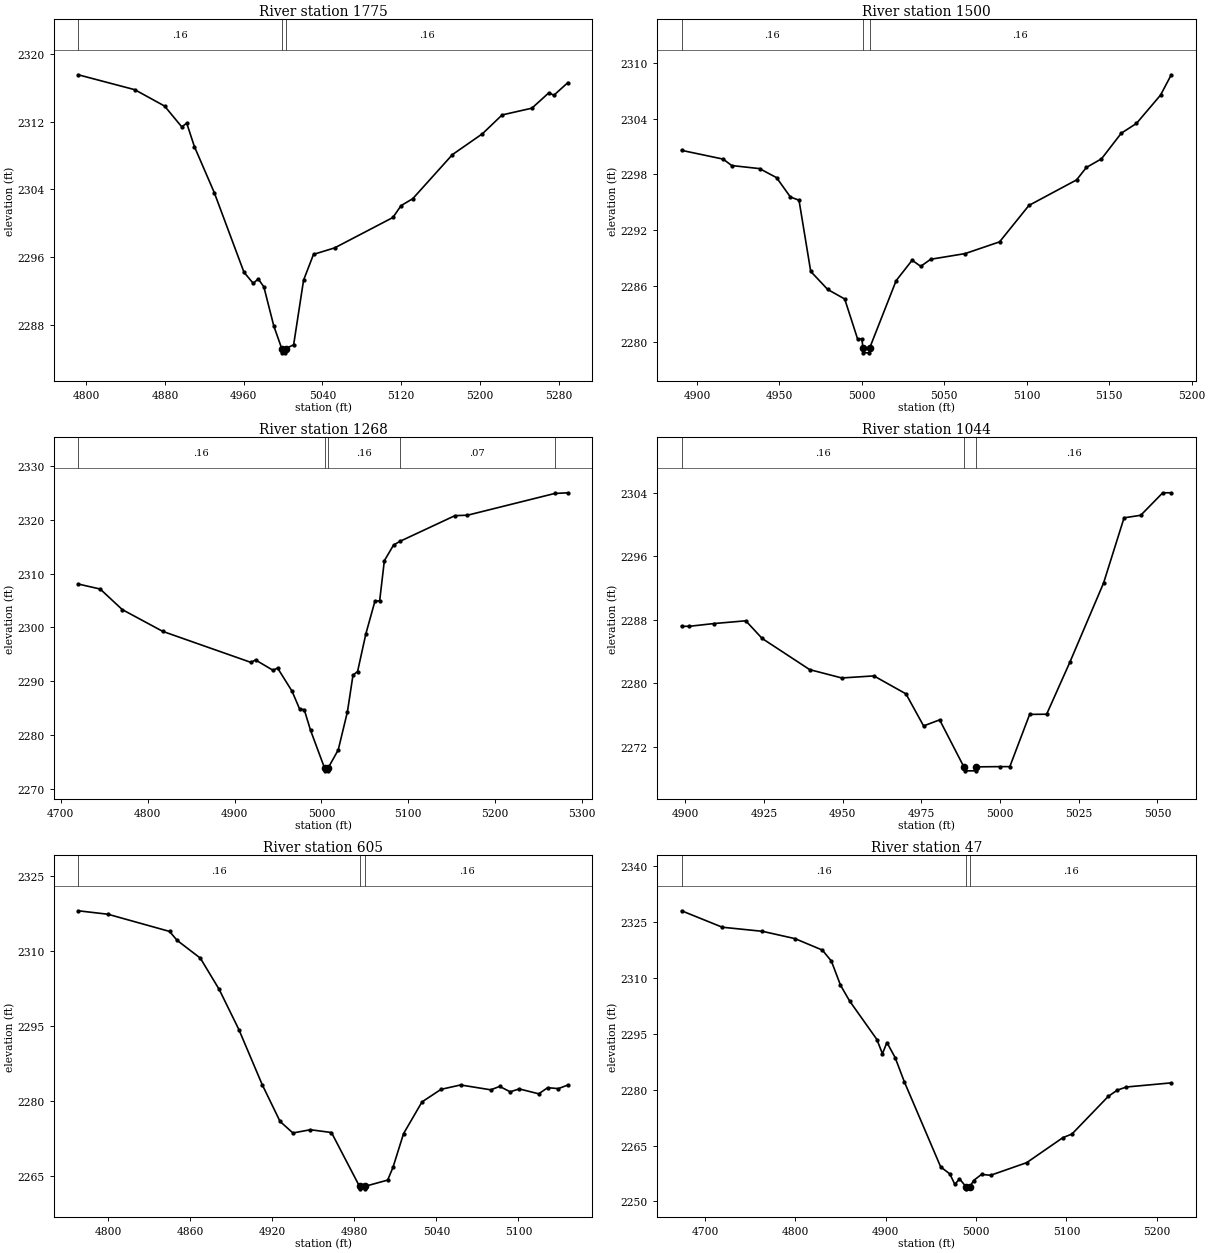
Type RM Length L Ch R = 1,1775,275,275,275
BEGIN DESCRIPTION:
843
END DESCRIPTION:
XS GIS Cut Line= 2
      1500562.01      6790348.57      1500068.70      6790415.30
#Sta/Elev= 30
  4791.7 2317.52  4849.2 2315.76  4879.5 2313.83  4897.0 2311.37  4902.0 2311.81
  4909.8 2309.05  4930.0 2303.62  4960.2 2294.22  4969.6 2292.91  4974.7 2293.43
  4980.4 2292.50  4990.5 2287.89  4998.6 2285.21  4998.8 2284.71  5002.3 2284.71
  5002.6 2285.21  5010.7 2285.66  5020.8 2293.29  5030.9 2296.33  5052.3 2297.09
  5111.6 2300.68  5119.9 2302.08  5131.8 2302.90  5172.1 2308.10  5202.6 2310.56
  5222.6 2312.78  5252.9 2313.58  5270.2 2315.40  5275.2 2315.10  5289.5 2316.60
#Mann=3,-1,0
  4791.7    0.16       0  4998.6    0.07       0  5002.6    0.16       0
Bank Sta=4998.6,5002.6
Exp/Cntr=0.3,0.1

Type RM Length L Ch R = 1,1500,232,232,232
BEGIN DESCRIPTION:
417
END DESCRIPTION:
XS GIS Cut Line= 4
      1500287.17      6790082.16      1500260.08      6790188.05
      1500230.20      6790287.15      1500159.52      6790332.70
#Sta/Elev= 30
  4890.7 2300.59  4915.9 2299.65  4921.1 2298.96  4938.0 2298.63  4948.3 2297.66
  4956.7 2295.58  4961.9 2295.24  4969.0 2287.60  4979.3 2285.66  4989.6 2284.64
  4997.4 2280.36  5000.0 2280.36  5000.7 2279.36  5001.0 2278.86  5004.5 2278.86
  5004.7 2279.36  5020.8 2286.61  5030.5 2288.80  5035.7 2288.14  5041.7 2288.90
  5062.6 2289.51  5083.5 2290.77  5101.3 2294.68  5130.2 2297.42  5136.1 2298.75
  5145.3 2299.68  5157.3 2302.43  5166.5 2303.48  5181.1 2306.52  5187.6 2308.70
#Mann=3,-1,0
  4890.7    0.16       0  5000.7    0.07       0  5004.7    0.16       0
Bank Sta=5000.7,5004.7
Exp/Cntr=0.3,0.1

Type RM Length L Ch R = 1,1268,224,224,224
BEGIN DESCRIPTION:
842
END DESCRIPTION:
XS GIS Cut Line= 2
      1500356.54      6789985.42      1499826.22      6790176.52
#Sta/Elev= 30
  4720.0 2308.05  4745.3 2307.12  4770.7 2303.31  4817.3 2299.27  4918.8 2293.52
  4924.1 2293.97  4944.2 2292.06  4949.5 2292.47  4966.1 2288.19  4974.9 2284.86
  4980.2 2284.75  4987.4 2280.95  5003.6 2273.91  5003.8 2273.41  5007.3 2273.41
  5007.6 2273.91  5019.3 2277.29  5029.9 2284.36  5036.3 2291.16  5041.6 2291.83
  5051.1 2298.80  5061.6 2304.89  5067.0 2304.93  5072.4 2312.37  5083.0 2315.28
  5090.3 2315.96  5153.7 2320.73  5168.1 2320.81  5268.5 2324.84  5283.7 2324.97
#Mann=5,-1,0
  4720.0    0.16       0  5003.6    0.07       0  5007.6    0.16       0
  5090.3    0.07       0  5268.5    0.16       0
Bank Sta=5003.6,5007.6
Exp/Cntr=0.3,0.1

Type RM Length L Ch R = 1,1044,439,439,439
BEGIN DESCRIPTION:
416
END DESCRIPTION:
XS GIS Cut Line= 3
      1500154.97      6789887.99      1500055.69      6789868.39
      1500004.96      6789888.02
#Sta/Elev= 25
  4898.8 2287.19  4901.3 2287.19  4909.0 2287.53  4919.2 2287.88  4924.4 2285.66
  4939.5 2281.74  4949.7 2280.69  4959.9 2280.95  4970.1 2278.69  4975.7 2274.66
  4980.8 2275.42  4988.5 2269.51  4988.8 2269.01  4992.3 2269.01  4992.5 2269.51
  5000.0 2269.54  5003.1 2269.54  5009.4 2276.11  5014.8 2276.13  5022.2 2282.69
  5032.9 2292.64  5039.4 2300.83  5044.7 2301.15  5051.7 2303.98  5054.4 2303.98
#Mann=3,-1,0
  4898.8    0.16       0  4988.5    0.07       0  4992.5    0.16       0
Bank Sta=4988.5,4992.5
Exp/Cntr=0.3,0.1

Type RM Length L Ch R = 1,605,558,558,558
BEGIN DESCRIPTION:
774
END DESCRIPTION:
XS GIS Cut Line= 3
      1500237.77      6789372.71      1500034.21      6789471.52
      1499933.42      6789556.50
#Sta/Elev= 30
  4778.1 2318.08  4799.8 2317.39  4844.9 2313.95  4850.4 2312.17  4867.4 2308.61
  4881.2 2302.35  4895.6 2294.32  4912.6 2283.34  4925.7 2275.96  4935.1 2273.65
  4947.9 2274.30  4963.3 2273.74  4983.8 2262.98  4984.1 2262.48  4987.6 2262.48
  4987.8 2262.98  5004.4 2264.23  5008.3 2266.79  5016.0 2273.51  5029.5 2279.86
  5043.4 2282.37  5057.7 2283.25  5079.8 2282.28  5086.3 2282.96  5094.0 2281.88
  5100.6 2282.46  5114.9 2281.48  5121.4 2282.71  5129.2 2282.52  5136.2 2283.24
#Mann=3,-1,0
  4778.1    0.16       0  4983.8    0.07       0  4987.8    0.16       0
Bank Sta=4983.8,4987.8
Exp/Cntr=0.3,0.1

Type RM Length L Ch R = 1,47,0,0,0
BEGIN DESCRIPTION:
415
END DESCRIPTION:
XS GIS Cut Line= 5
      1500059.88      6789084.19      1499941.33      6789096.05
      1499737.78      6789070.36      1499730.00      6789213.00
      1499733.83      6789287.75
#Sta/Elev= 30
  4674.0 2327.91  4719.1 2323.50  4763.4 2322.41  4799.5 2320.45  4829.8 2317.38
  4839.8 2314.43  4849.9 2307.97  4860.0 2303.73  4890.2 2293.41  4896.3 2289.59
  4901.3 2292.60  4910.4 2288.56  4920.5 2282.11  4960.8 2259.26  4970.9 2257.40
  4976.5 2254.56  4981.6 2256.08  4989.0 2253.89  4989.3 2253.39  4993.0 2253.89
  4997.2 2255.62  5006.0 2257.26  5016.0 2257.02  5056.0 2260.41  5096.1 2267.12
  5106.1 2268.08  5146.2 2278.15  5156.2 2279.83  5166.2 2280.68  5216.0 2281.79
#Mann=3,-1,0
  4674.0    0.16       0  4989.0    0.07       0  4993.0    0.16       0
Bank Sta=4989,4993
Exp/Cntr=0.3,0.1

Chan Stop Cuts=-1