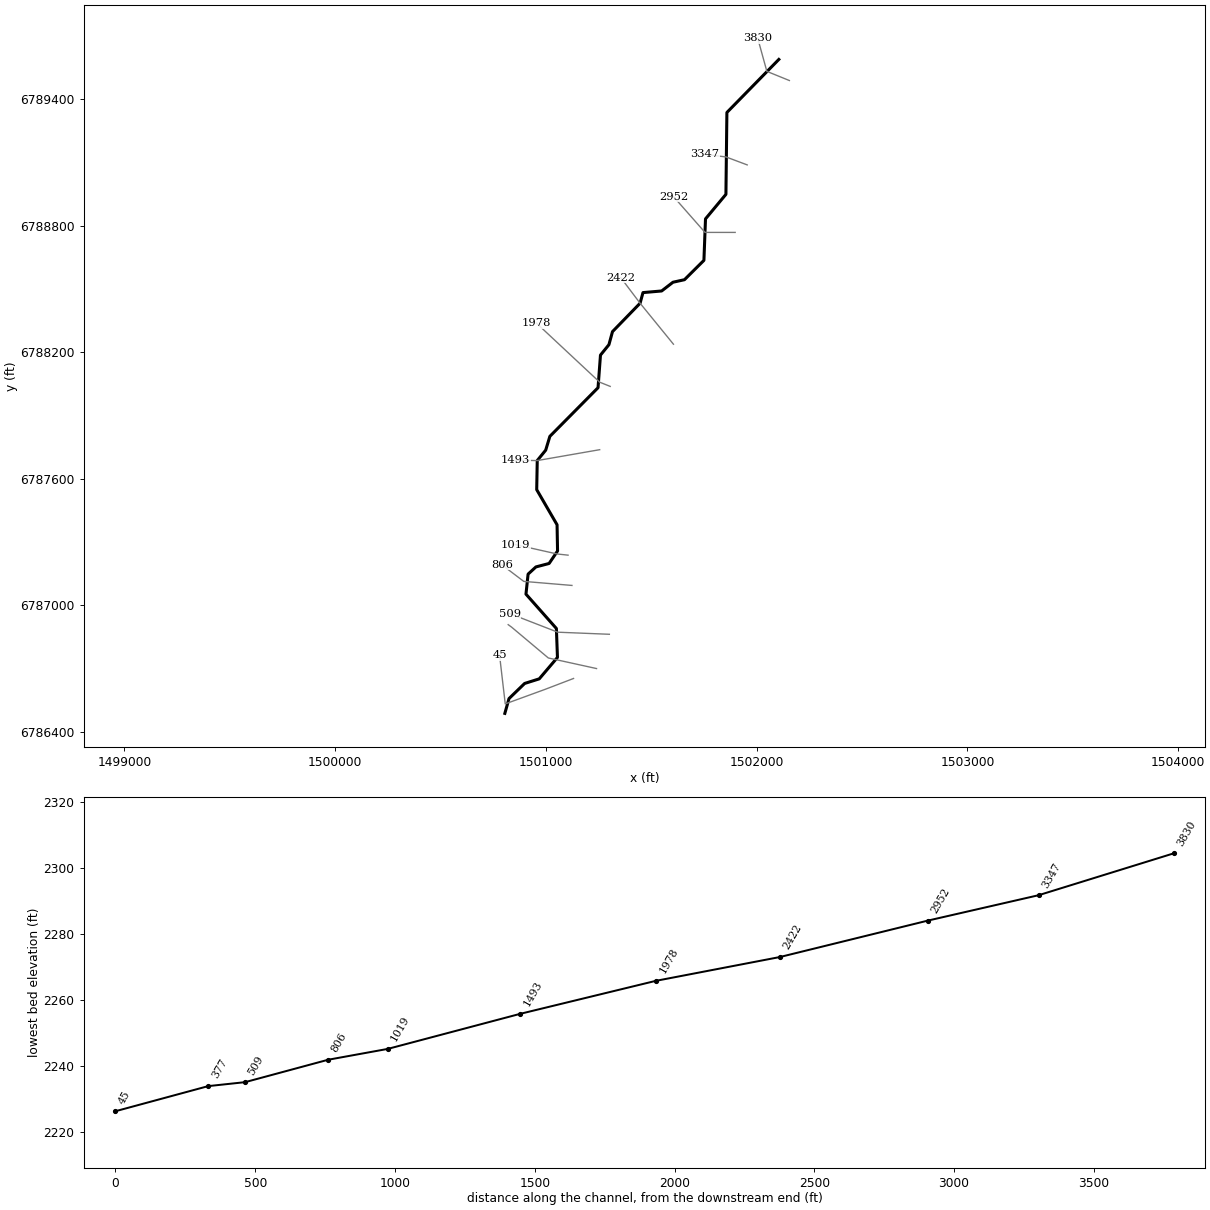
--- Elm 25.prj (project) ---

Proj Title=Elm 25 Base Level Engineering
Current Plan=p01
Default Exp/Contr=0.3,0.1
English Units
Geom File=g01
Flow File=f01
Plan File=p01
BEGIN DESCRIPTION:
Elm 25
END DESCRIPTION:

--- Elm 25.p01 (plan) ---

Plan Title=Multiple Run
Short Identifier=Multiple
Geom File=g01
Flow File=f01
Subcritical Flow
K Sum by GR= 0
Std Step Tol= 0.01
Critical Tol= 0.01
Num of Std Step Trials= 20
Max Error Tol= 0.3
Flow Tol Ratio= 0.001
Split Flow NTrial= 30
Split Flow Tol= 0.02
Split Flow Ratio= 0.02
Log Output Level= 0
Friction Slope Method= 1
Unsteady Friction Slope Method= 2
Unsteady Bridges Friction Slope Method= 1
Parabolic Critical Depth
Global Vel Dist=  1 , 1 , 1
Global Log Level= 0
CheckData=True
Encroach Param= -1, 0, 0, 0
BEGIN DESCRIPTION:
Multiple Run
END DESCRIPTION:

--- Elm 25.f01 (steady flow) ---

Flow Title=Multiple
Number of Profiles=7
Profile Names=10-year,25-year,50-year,1pct_min,100-year,1pct_plu,500-year
River Rch & RM= Elm 25,Reach-1,3830
     181     248     303     230     369     507     552
Boundary for River Rch & Prof#=Elm 25,Reach-1,1
Up Type=0
Dn Type=3
Dn Slope=0.005
Boundary for River Rch & Prof#=Elm 25,Reach-1,2
Up Type=0
Dn Type=3
Dn Slope=0.005
Boundary for River Rch & Prof#=Elm 25,Reach-1,3
Up Type=0
Dn Type=3
Dn Slope=0.005
Boundary for River Rch & Prof#=Elm 25,Reach-1,4
Up Type=0
Dn Type=3
Dn Slope=0.005
Boundary for River Rch & Prof#=Elm 25,Reach-1,5
Up Type=0
Dn Type=3
Dn Slope=0.005
Boundary for River Rch & Prof#=Elm 25,Reach-1,6
Up Type=0
Dn Type=3
Dn Slope=0.005
Boundary for River Rch & Prof#=Elm 25,Reach-1,7
Up Type=0
Dn Type=3
Dn Slope=0.005

--- Elm 25.g01 (geometry) ---

Geom Title=Existing Conditions

River Reach=Elm 25,Reach-1
Reach XY= 30
      1502105.00      6789588.00      1501858.54      6789336.54
      1501853.94      6788948.44      1501757.07      6788832.14
      1501749.55      6788635.53      1501657.31      6788543.82
      1501602.83      6788531.86      1501548.95      6788490.37
      1501460.47      6788482.74      1501446.70      6788432.30
      1501315.76      6788297.68      1501298.86      6788235.83
      1501258.76      6788186.44      1501247.18      6788031.81
      1501018.62      6787801.22      1500998.86      6787735.83
      1500958.74      6787686.44      1500956.19      6787548.50
      1501052.77      6787382.07      1501055.11      6787257.89
      1501015.04      6787198.63      1500952.45      6787182.25
      1500915.30      6787148.10      1500905.23      6787053.22
      1501049.55      6786890.45      1501054.64      6786753.16
      1500968.24      6786651.62      1500898.94      6786629.85
      1500824.76      6786558.14      1500805.00      6786488.00

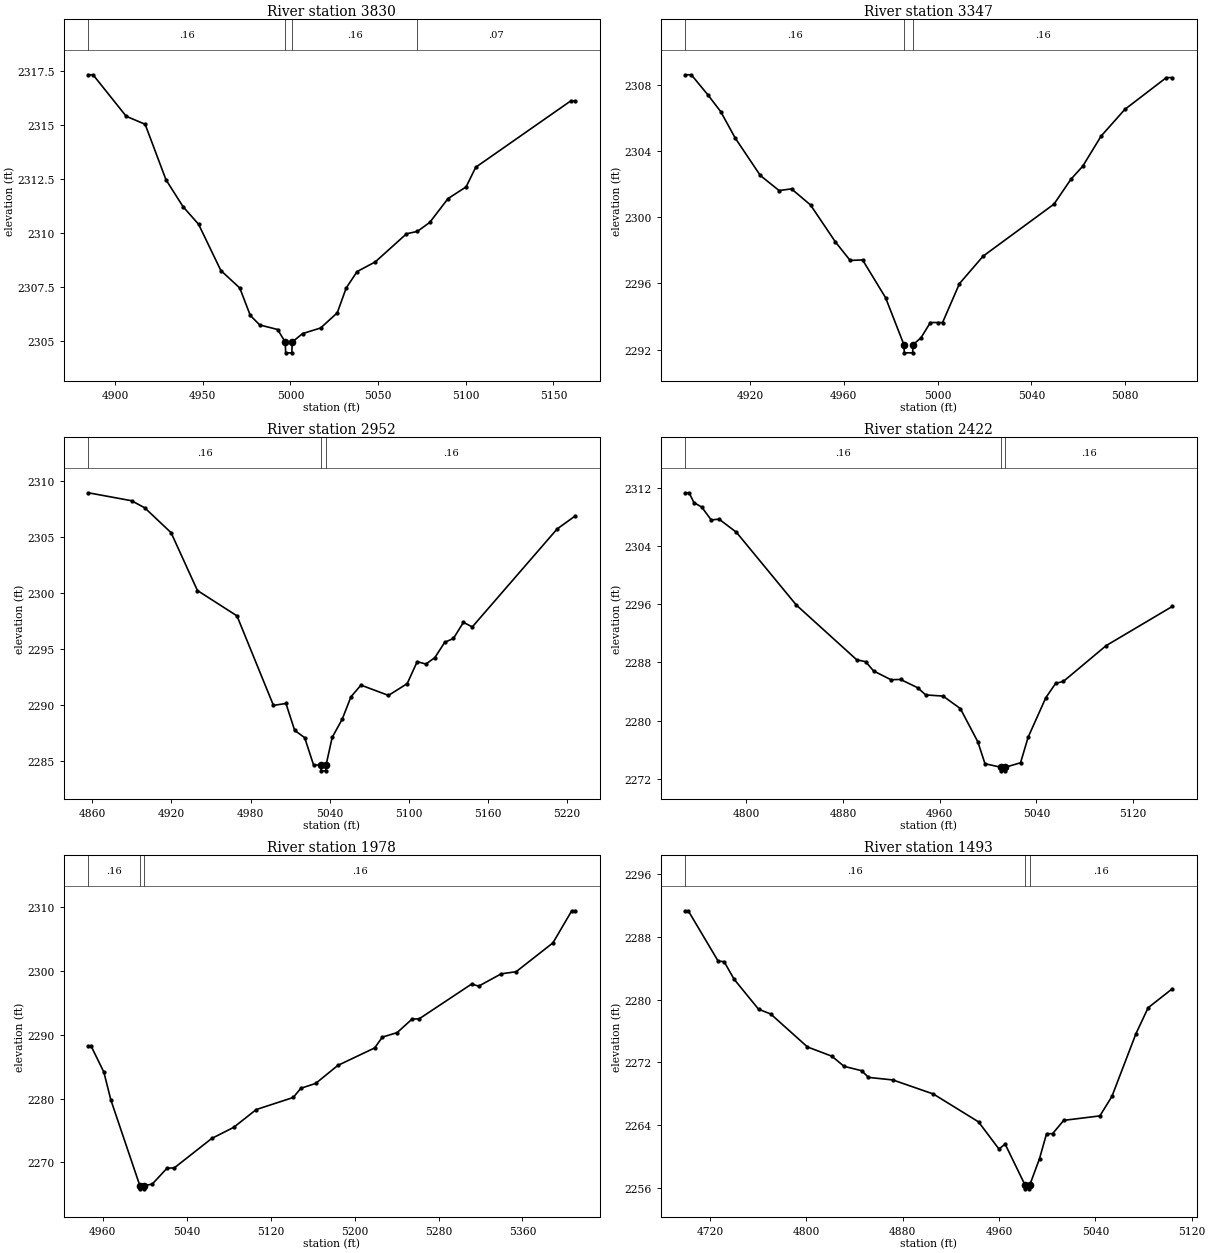
Type RM Length L Ch R = 1,3830,483,483,483
BEGIN DESCRIPTION:
458
END DESCRIPTION:
XS GIS Cut Line= 3
      1502155.04      6789487.99      1502048.21      6789531.38
      1502004.99      6789688.03
#Sta/Elev= 30
  4884.7 2317.34  4887.4 2317.34  4906.3 2315.42  4917.1 2315.05  4929.0 2312.48
  4938.7 2311.24  4947.6 2310.42  4960.3 2308.28  4971.1 2307.47  4977.1 2306.20
  4982.5 2305.76  4992.7 2305.55  4997.0 2304.97  4997.3 2304.47  5000.8 2304.47
  5001.0 2304.97  5006.9 2305.36  5017.2 2305.62  5026.7 2306.32  5031.8 2307.47
  5038.0 2308.23  5048.4 2308.68  5066.2 2309.98  5072.4 2310.09  5079.5 2310.51
  5089.9 2311.61  5100.2 2312.15  5105.7 2313.06  5159.9 2316.13  5162.5 2316.13
#Mann=4,-1,0
  4884.7    0.16       0  4997.0    0.07       0  5001.0    0.16       0
  5072.4    0.07       0
Bank Sta=4997,5001
Exp/Cntr=0.3,0.1

Type RM Length L Ch R = 1,3347,395,395,395
BEGIN DESCRIPTION:
457
END DESCRIPTION:
XS GIS Cut Line= 3
      1501954.97      6789088.01      1501854.23      6789125.82
      1501754.97      6789138.00
#Sta/Elev= 30
  4892.4 2308.59  4895.0 2308.59  4902.1 2307.37  4907.5 2306.37  4913.7 2304.77
  4924.4 2302.51  4932.4 2301.60  4937.7 2301.70  4945.8 2300.73  4956.4 2298.50
  4962.7 2297.38  4968.0 2297.41  4977.8 2295.13  4985.6 2292.30  4985.8 2291.80
  4989.3 2291.80  4989.6 2292.30  4992.9 2292.71  4996.9 2293.63  5000.0 2293.63
  5002.1 2293.63  5009.3 2295.98  5019.4 2297.64  5049.6 2300.78  5056.8 2302.28
  5061.8 2303.06  5069.7 2304.89  5079.8 2306.50  5097.5 2308.42  5100.0 2308.42
#Mann=3,-1,0
  4892.4    0.16       0  4985.6    0.07       0  4989.6    0.16       0
Bank Sta=4985.6,4989.6
Exp/Cntr=0.3,0.1

Type RM Length L Ch R = 1,2952,530,530,530
BEGIN DESCRIPTION:
456
END DESCRIPTION:
XS GIS Cut Line= 3
      1501897.81      6788768.00      1501754.71      6788768.03
      1501605.00      6788938.00
#Sta/Elev= 30
  4856.9 2308.94  4889.7 2308.23  4899.7 2307.60  4919.7 2305.38  4939.7 2300.22
  4969.7 2297.96  4997.4 2289.97  5006.9 2290.14  5013.5 2287.74  5021.1 2287.09
  5027.8 2284.67  5033.3 2284.63  5033.6 2284.13  5037.1 2284.13  5037.3 2284.63
  5042.0 2287.12  5049.6 2288.74  5056.2 2290.73  5063.8 2291.78  5084.7 2290.86
  5098.9 2291.91  5106.5 2293.87  5113.1 2293.66  5119.9 2294.23  5127.4 2295.60
  5134.0 2295.94  5141.6 2297.38  5148.3 2296.97  5212.7 2305.71  5226.5 2306.88
#Mann=3,-1,0
  4856.9    0.16       0  5033.3    0.07       0  5037.3    0.16       0
Bank Sta=5033.3,5037.3
Exp/Cntr=0.3,0.1

Type RM Length L Ch R = 1,2422,444,444,444
BEGIN DESCRIPTION:
455
END DESCRIPTION:
XS GIS Cut Line= 3
      1501604.99      6788238.02      1501446.70      6788432.30
      1501354.88      6788553.81
#Sta/Elev= 30
  4749.4 2311.35  4752.6 2311.35  4756.6 2309.99  4763.0 2309.39  4770.9 2307.61
  4777.4 2307.72  4791.7 2305.92  4841.3 2295.90  4891.3 2288.36  4898.7 2288.10
  4905.2 2286.83  4919.6 2285.62  4927.5 2285.66  4941.8 2284.51  4948.3 2283.53
  4962.7 2283.37  4977.0 2281.65  4991.4 2277.10  4997.4 2274.06  5010.3 2273.58
  5010.5 2273.08  5014.0 2273.08  5014.3 2273.58  5026.8 2274.19  5033.1 2277.71
  5047.7 2283.14  5055.9 2285.13  5062.2 2285.38  5097.6 2290.31  5152.3 2295.70
#Mann=3,-1,0
  4749.4    0.16       0  5010.3    0.07       0  5014.3    0.16       0
Bank Sta=5010.3,5014.3
Exp/Cntr=0.3,0.1

Type RM Length L Ch R = 1,1978,485,485,485
BEGIN DESCRIPTION:
454
END DESCRIPTION:
XS GIS Cut Line= 3
      1501304.97      6788038.01      1501255.02      6788057.99
      1500954.99      6788338.01
#Sta/Elev= 30
  4946.2 2288.24  4948.9 2288.24  4961.0 2284.17  4967.7 2279.79  4995.3 2266.36
  4995.6 2265.86  4999.1 2265.86  4999.3 2266.36  5007.1 2266.60  5021.3 2269.11
  5028.1 2269.14  5063.8 2273.76  5084.8 2275.51  5106.3 2278.30  5141.5 2280.19
  5148.8 2281.64  5162.9 2282.39  5184.0 2285.22  5219.1 2287.96  5226.5 2289.66
  5240.6 2290.37  5254.8 2292.49  5261.6 2292.53  5311.5 2297.98  5318.3 2297.66
  5339.8 2299.59  5354.0 2299.92  5389.1 2304.45  5407.0 2309.48  5410.4 2309.48
#Mann=3,-1,0
  4946.2    0.16       0  4995.3    0.07       0  4999.3    0.16       0
Bank Sta=4995.3,4999.3
Exp/Cntr=0.3,0.1

Type RM Length L Ch R = 1,1493,474,474,474
BEGIN DESCRIPTION:
453
END DESCRIPTION:
XS GIS Cut Line= 3
      1501254.99      6787738.00      1500958.74      6787686.44
      1500854.95      6787688.00
#Sta/Elev= 30
  4699.3 2291.32  4701.8 2291.32  4726.6 2284.91  4731.6 2284.83  4739.9 2282.59
  4760.2 2278.77  4770.3 2278.16  4800.8 2273.96  4821.1 2272.78  4831.2 2271.49
  4845.8 2270.93  4851.5 2270.08  4871.8 2269.75  4905.4 2267.96  4942.9 2264.41
  4959.9 2260.94  4965.0 2261.58  4981.5 2256.37  4981.7 2255.87  4985.2 2255.87
  4985.5 2256.37  4993.6 2259.73  4999.4 2262.90  5004.4 2262.90  5013.7 2264.60
  5043.7 2265.17  5053.7 2267.65  5073.7 2275.66  5083.8 2278.96  5103.8 2281.37
#Mann=3,-1,0
  4699.3    0.16       0  4981.5    0.07       0  4985.5    0.16       0
Bank Sta=4981.5,4985.5
Exp/Cntr=0.3,0.1

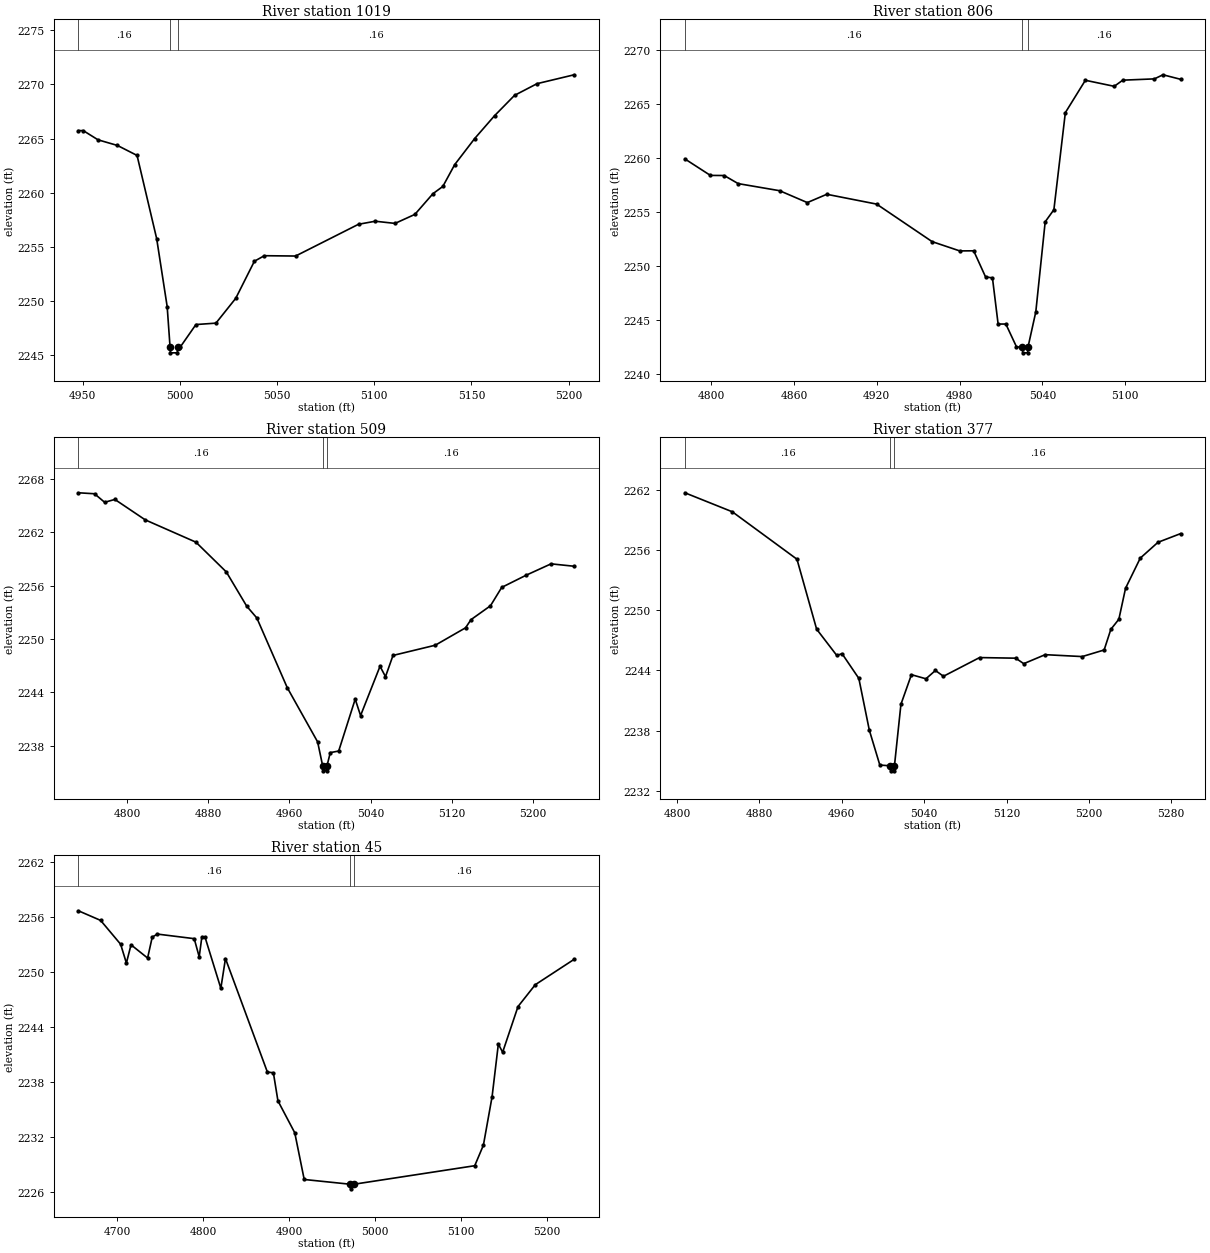
Type RM Length L Ch R = 1,1019,213,213,213
BEGIN DESCRIPTION:
452
END DESCRIPTION:
XS GIS Cut Line= 3
      1501105.02      6787238.00      1501053.03      6787243.68
      1500855.03      6787287.99
#Sta/Elev= 30
  4947.7 2265.74  4950.2 2265.74  4957.8 2264.89  4967.8 2264.37  4977.9 2263.45
  4988.0 2255.77  4993.4 2249.51  4994.9 2245.74  4995.1 2245.24  4998.6 2245.24
  4998.9 2245.74  5000.0 2245.74  5008.2 2247.85  5018.5 2247.98  5028.7 2250.27
  5038.3 2253.69  5043.4 2254.20  5059.5 2254.17  5091.9 2257.10  5100.5 2257.38
  5110.7 2257.18  5120.9 2258.01  5130.2 2259.92  5135.3 2260.59  5141.4 2262.60
  5151.7 2265.01  5161.9 2267.11  5172.2 2268.99  5183.8 2270.07  5202.9 2270.89
#Mann=3,-1,0
  4947.7    0.16       0  4994.9    0.07       0  4998.9    0.16       0
Bank Sta=4994.9,4998.9
Exp/Cntr=0.3,0.1

Type RM Length L Ch R = 1,806,297,297,297
BEGIN DESCRIPTION:
845
END DESCRIPTION:
XS GIS Cut Line= 3
      1501123.43      6787094.49      1500894.70      6787113.68
      1500791.40      6787191.89
#Sta/Elev= 30
  4781.0 2259.94  4799.5 2258.41  4809.5 2258.40  4819.6 2257.65  4849.7 2256.99
  4869.7 2255.89  4883.8 2256.66  4919.9 2255.75  4960.1 2252.27  4980.1 2251.41
  4990.2 2251.42  4998.8 2249.00  5003.8 2248.91  5007.9 2244.63  5013.5 2244.63
  5021.2 2242.52  5025.5 2242.46  5025.7 2241.96  5029.2 2241.96  5029.5 2242.46
  5035.2 2245.76  5042.0 2254.11  5048.3 2255.23  5056.6 2264.23  5071.1 2267.23
  5092.0 2266.67  5098.2 2267.24  5121.1 2267.36  5127.3 2267.74  5140.1 2267.32
#Mann=3,-1,0
  4781.0    0.16       0  5025.5    0.07       0  5029.5    0.16       0
Bank Sta=5025.5,5029.5
Exp/Cntr=0.3,0.1

Type RM Length L Ch R = 1,509,132,132,132
BEGIN DESCRIPTION:
773
END DESCRIPTION:
XS GIS Cut Line= 3
      1501300.93      6786862.95      1501055.91      6786872.83
      1500828.35      6786961.10
#Sta/Elev= 30
  4751.7 2266.47  4767.6 2266.36  4777.6 2265.40  4787.7 2265.72  4817.7 2263.42
  4867.7 2260.91  4897.7 2257.56  4917.8 2253.71  4927.8 2252.38  4957.8 2244.54
  4987.8 2238.43  4992.9 2235.67  4993.1 2235.17  4996.6 2235.17  4996.9 2235.67
  5000.3 2237.22  5008.6 2237.40  5024.9 2243.24  5030.2 2241.39  5049.4 2246.94
  5054.8 2245.77  5062.2 2248.16  5103.9 2249.31  5133.8 2251.27  5139.2 2252.19
  5158.4 2253.75  5169.5 2255.82  5193.6 2257.19  5218.2 2258.47  5241.0 2258.20
#Mann=3,-1,0
  4751.7    0.16       0  4992.9    0.07       0  4996.9    0.16       0
Bank Sta=4992.9,4996.9
Exp/Cntr=0.3,0.1

Type RM Length L Ch R = 1,377,332,332,332
BEGIN DESCRIPTION:
844
END DESCRIPTION:
XS GIS Cut Line= 4
      1501240.03      6786700.48      1501011.28      6786750.65
      1500837.15      6786896.75      1500820.88      6786908.58
#Sta/Elev= 30
  4807.5 2261.76  4853.6 2259.86  4916.4 2255.12  4935.5 2248.13  4955.1 2245.50
  4960.2 2245.68  4976.5 2243.21  4986.7 2238.03  4996.9 2234.55  5007.1 2234.47
  5007.4 2233.97  5010.9 2233.97  5011.1 2234.47  5017.4 2240.62  5027.6 2243.58
  5041.7 2243.17  5050.9 2244.00  5058.7 2243.42  5093.8 2245.29  5128.9 2245.23
  5136.7 2244.68  5157.5 2245.58  5193.5 2245.39  5214.8 2246.05  5221.3 2248.11
  5229.1 2249.12  5235.6 2252.22  5249.9 2255.23  5267.1 2256.81  5289.1 2257.68
#Mann=3,-1,0
  4807.5    0.16       0  5007.1    0.07       0  5011.1    0.16       0
Bank Sta=5007.1,5011.1
Exp/Cntr=0.3,0.1

Type RM Length L Ch R = 1,45,0,0,0
BEGIN DESCRIPTION:
451
END DESCRIPTION:
XS GIS Cut Line= 4
      1501130.97      6786653.46      1500996.62      6786602.09
      1500806.91      6786532.92      1500780.00      6786762.99
#Sta/Elev= 30
  4654.6 2256.67  4680.5 2255.62  4703.8 2253.02  4710.5 2250.97  4715.9 2252.96
  4735.2 2251.52  4740.6 2253.80  4746.6 2254.13  4789.5 2253.63  4795.3 2251.65
  4798.4 2253.82  4802.0 2253.82  4820.5 2248.22  4825.9 2251.46  4874.7 2239.09
  4881.7 2239.01  4887.0 2235.95  4906.6 2232.47  4917.6 2227.38  4971.4 2226.86
  4971.6 2226.36  4975.4 2226.86  5116.2 2228.88  5126.3 2231.12  5136.4 2236.40
  5143.7 2242.14  5148.7 2241.25  5166.6 2246.23  5186.7 2248.61  5232.0 2251.38
#Mann=3,-1,0
  4654.6    0.16       0  4971.4    0.07       0  4975.4    0.16       0
Bank Sta=4971.4,4975.4
Exp/Cntr=0.3,0.1

Chan Stop Cuts=-1