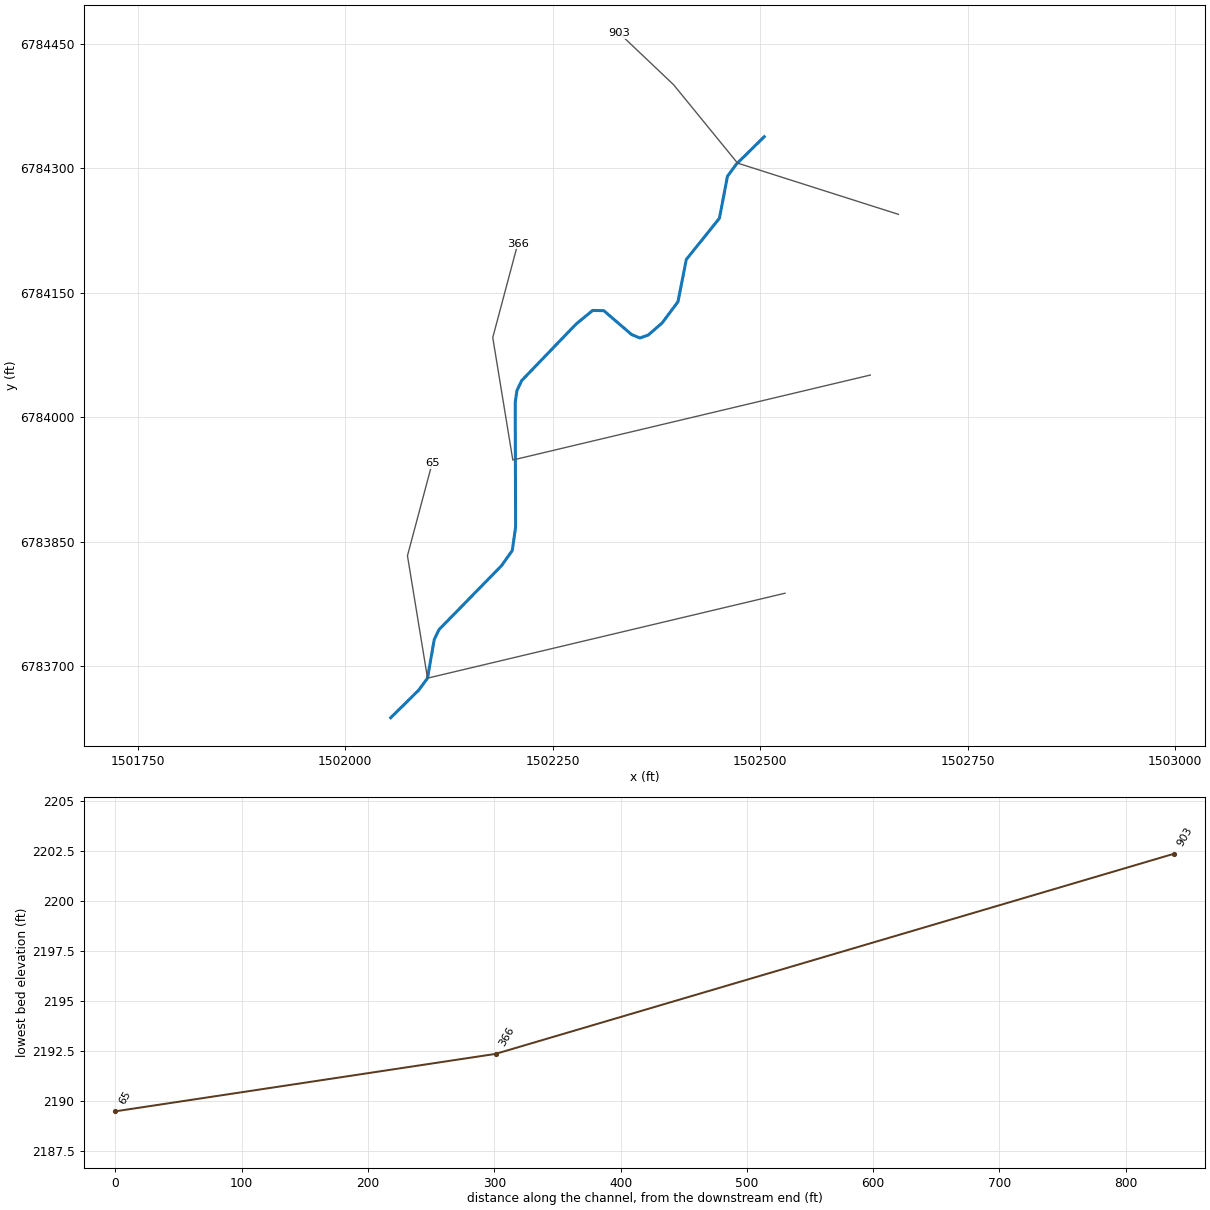
--- Elm 26.prj (project) ---

Proj Title=Elm 26 Base Level Engineering
Current Plan=p01
Default Exp/Contr=0.3,0.1
English Units
Geom File=g01
Flow File=f01
Plan File=p01
BEGIN DESCRIPTION:
Elm 26
END DESCRIPTION:

--- Elm 26.p01 (plan) ---

Plan Title=Multiple Run
Short Identifier=Multiple
Geom File=g01
Flow File=f01
Subcritical Flow
K Sum by GR= 0
Std Step Tol= 0.01
Critical Tol= 0.01
Num of Std Step Trials= 20
Max Error Tol= 0.3
Flow Tol Ratio= 0.001
Split Flow NTrial= 30
Split Flow Tol= 0.02
Split Flow Ratio= 0.02
Log Output Level= 0
Friction Slope Method= 1
Unsteady Friction Slope Method= 2
Unsteady Bridges Friction Slope Method= 1
Parabolic Critical Depth
Global Vel Dist=  1 , 1 , 1
Global Log Level= 0
CheckData=True
Encroach Param= -1, 0, 0, 0
BEGIN DESCRIPTION:
Multiple Run
END DESCRIPTION:

--- Elm 26.f01 (steady flow) ---

Flow Title=Multiple
Number of Profiles=7
Profile Names=10-year,25-year,50-year,1pct_min,100-year,1pct_plu,500-year
River Rch & RM= Elm 26,Reach-1,903
     173     236     289     219     351     483     525
Boundary for River Rch & Prof#=Elm 26,Reach-1,1
Up Type=0
Dn Type=3
Dn Slope=0.005
Boundary for River Rch & Prof#=Elm 26,Reach-1,2
Up Type=0
Dn Type=3
Dn Slope=0.005
Boundary for River Rch & Prof#=Elm 26,Reach-1,3
Up Type=0
Dn Type=3
Dn Slope=0.005
Boundary for River Rch & Prof#=Elm 26,Reach-1,4
Up Type=0
Dn Type=3
Dn Slope=0.005
Boundary for River Rch & Prof#=Elm 26,Reach-1,5
Up Type=0
Dn Type=3
Dn Slope=0.005
Boundary for River Rch & Prof#=Elm 26,Reach-1,6
Up Type=0
Dn Type=3
Dn Slope=0.005
Boundary for River Rch & Prof#=Elm 26,Reach-1,7
Up Type=0
Dn Type=3
Dn Slope=0.005

--- Elm 26.g01 (geometry) ---

Geom Title=Existing Conditions

River Reach=Elm 26,Reach-1
Reach XY= 26
      1502505.00      6784338.00      1502471.41      6784304.93
      1502460.67      6784290.36      1502450.96      6784239.67
      1502411.10      6784190.14      1502401.05      6784139.17
      1502381.99      6784113.64      1502365.32      6784099.11
      1502355.21      6784095.47      1502345.13      6784099.65
      1502311.68      6784128.38      1502298.32      6784128.70
      1502278.27      6784112.25      1502212.81      6784044.23
      1502207.06      6784032.17      1502204.96      6784018.03
      1502205.19      6783942.92      1502205.43      6783867.82
      1502201.45      6783839.47      1502188.54      6783821.25
      1502150.81      6783782.67      1502113.07      6783744.08
      1502107.35      6783732.03      1502099.30      6783685.65
      1502088.58      6783671.08      1502055.00      6783638.00

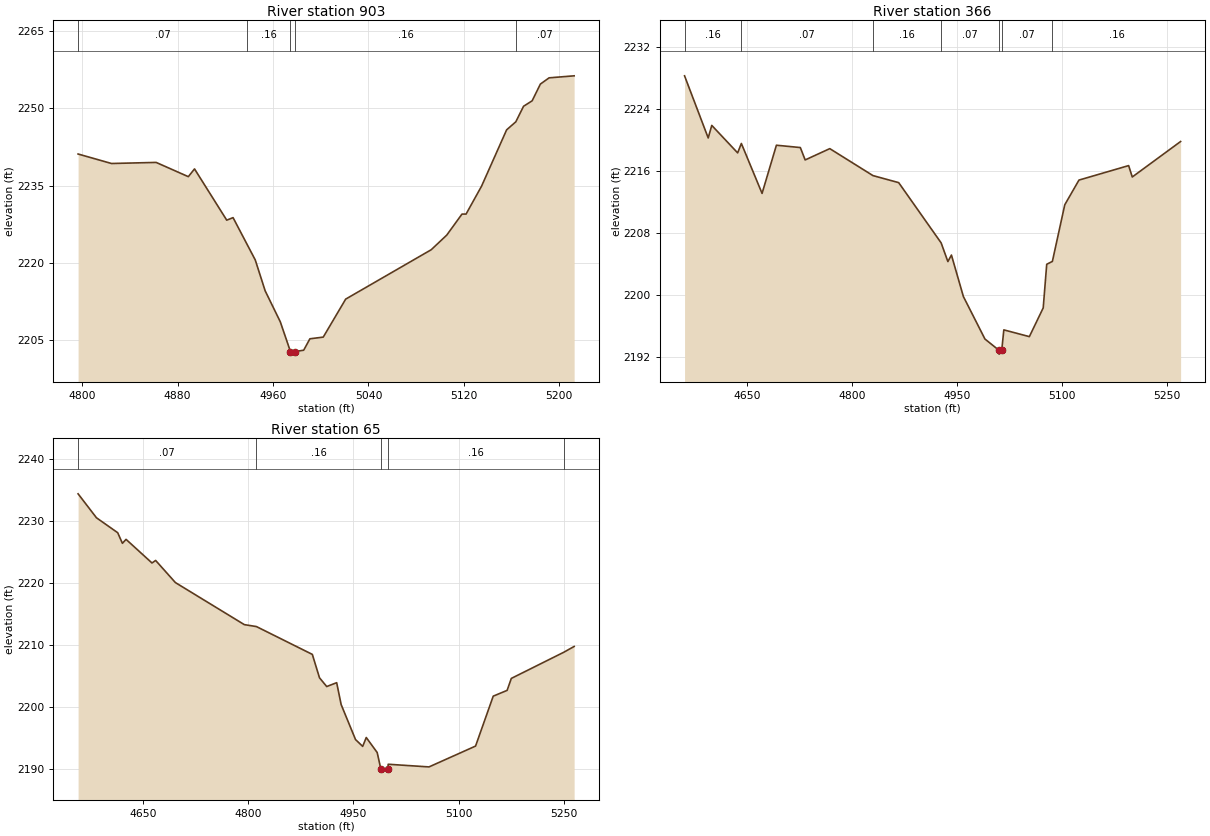
Type RM Length L Ch R = 1,903,537,537,537
BEGIN DESCRIPTION:
772
END DESCRIPTION:
XS GIS Cut Line= 4
      1502666.52      6784244.48      1502472.80      6784306.17
      1502395.77      6784400.60      1502330.02      6784462.98
#Sta/Elev= 30
  4796.6 2241.12  4824.6 2239.28  4862.0 2239.49  4889.0 2236.73  4894.2 2238.23
  4921.2 2228.30  4926.5 2228.79  4938.3 2223.59  4945.1 2220.60  4953.4 2214.61
  4966.1 2208.60  4974.6 2202.84  4974.9 2202.34  4978.6 2202.84  4985.7 2203.10
  4990.9 2205.31  5002.1 2205.64  5020.9 2213.00  5092.6 2222.57  5105.6 2225.40
  5118.4 2229.48  5121.8 2229.48  5134.8 2234.89  5155.8 2245.80  5163.5 2247.36
  5170.0 2250.37  5177.2 2251.43  5184.1 2254.67  5191.4 2255.88  5212.4 2256.27
#Mann=5,-1,0
  4796.6    0.07       0  4938.3    0.16       0  4974.6    0.07       0
  4978.6    0.16       0  5163.5    0.07       0
Bank Sta=4974.6,4978.6
Exp/Cntr=0.3,0.1

Type RM Length L Ch R = 1,366,301,301,301
BEGIN DESCRIPTION:
771
END DESCRIPTION:
XS GIS Cut Line= 4
      1502632.77      6784050.82      1502202.06      6783948.48
      1502177.89      6784095.97      1502208.04      6784208.96
#Sta/Elev= 30
  4560.5 2228.27  4594.3 2220.25  4599.4 2221.87  4636.4 2218.32  4641.7 2219.54
  4671.3 2213.09  4691.8 2219.31  4726.0 2219.01  4732.9 2217.41  4768.1 2218.87
  4829.8 2215.39  4866.6 2214.48  4927.3 2206.70  4936.9 2204.29  4942.0 2205.13
  4959.1 2199.77  4989.9 2194.29  5009.9 2192.84  5010.1 2192.34  5013.9 2192.84
  5016.9 2195.47  5053.4 2194.60  5073.2 2198.31  5078.2 2203.94  5086.3 2204.31
  5104.0 2211.62  5124.3 2214.81  5195.3 2216.68  5200.5 2215.21  5269.6 2219.79
#Mann=7,-1,0
  4560.5    0.16       0  4641.7    0.07       0  4829.8    0.16       0
  4927.3    0.07       0  5009.9    0.07       0  5013.9    0.07       0
  5086.3    0.16       0
Bank Sta=5009.9,5013.9
Exp/Cntr=0.3,0.1

Type RM Length L Ch R = 1,65,0,0,0
BEGIN DESCRIPTION:
770
END DESCRIPTION:
XS GIS Cut Line= 4
      1502530.01      6783787.98      1502099.30      6783685.65
      1502075.13      6783833.13      1502104.87      6783944.58
#Sta/Elev= 30
  4557.3 2234.34  4583.5 2230.48  4613.8 2228.07  4620.5 2226.36  4625.7 2227.00
  4662.7 2223.19  4667.9 2223.60  4696.1 2220.03  4794.4 2213.25  4811.6 2212.94
  4891.4 2208.45  4901.6 2204.68  4911.9 2203.27  4926.1 2203.89  4932.5 2200.36
  4953.0 2194.72  4963.2 2193.62  4968.3 2195.05  4983.9 2192.63  4989.1 2189.97
  4989.6 2189.47  4999.1 2189.97  4999.6 2190.74  5057.8 2190.31  5124.2 2193.67
  5149.4 2201.72  5169.2 2202.65  5175.2 2204.58  5249.9 2208.79  5264.8 2209.73
#Mann=5,-1,0
  4557.3    0.07       0  4811.6    0.16       0  4989.1    0.07       0
  4999.1    0.16       0  5249.9    0.07       0
Bank Sta=4989.1,4999.1
Exp/Cntr=0.3,0.1

Chan Stop Cuts=-1