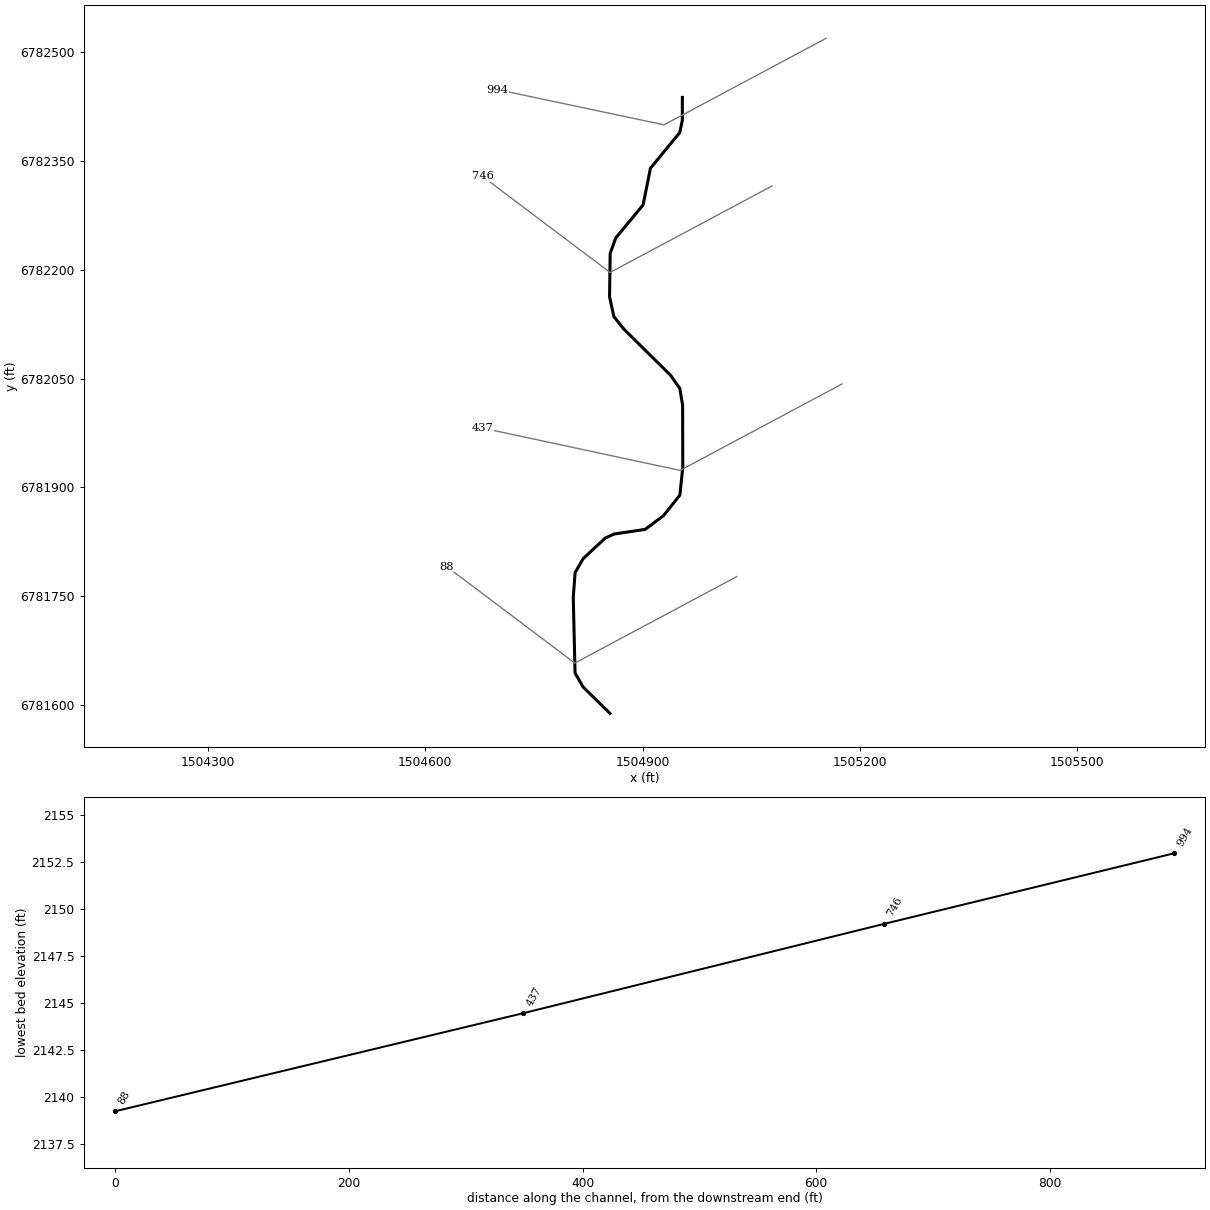
--- Elm 27.prj (project) ---

Proj Title=Elm 27 Base Level Engineering
Current Plan=p01
Default Exp/Contr=0.3,0.1
English Units
Geom File=g01
Flow File=f01
Plan File=p01
BEGIN DESCRIPTION:
Elm 27
END DESCRIPTION:

--- Elm 27.p01 (plan) ---

Plan Title=Multiple Run
Short Identifier=Multiple
Geom File=g01
Flow File=f01
Subcritical Flow
K Sum by GR= 0
Std Step Tol= 0.01
Critical Tol= 0.01
Num of Std Step Trials= 20
Max Error Tol= 0.3
Flow Tol Ratio= 0.001
Split Flow NTrial= 30
Split Flow Tol= 0.02
Split Flow Ratio= 0.02
Log Output Level= 0
Friction Slope Method= 1
Unsteady Friction Slope Method= 2
Unsteady Bridges Friction Slope Method= 1
Parabolic Critical Depth
Global Vel Dist=  1 , 1 , 1
Global Log Level= 0
CheckData=True
Encroach Param= -1, 0, 0, 0
BEGIN DESCRIPTION:
Multiple Run
END DESCRIPTION:

--- Elm 27.f01 (steady flow) ---

Flow Title=Multiple
Number of Profiles=7
Profile Names=10-year,25-year,50-year,1pct_min,100-year,1pct_plu,500-year
River Rch & RM= Elm 27,Reach-1,994
     127     172     208     157     252     347     372
Boundary for River Rch & Prof#=Elm 27,Reach-1,1
Up Type=0
Dn Type=3
Dn Slope=0.005
Boundary for River Rch & Prof#=Elm 27,Reach-1,2
Up Type=0
Dn Type=3
Dn Slope=0.005
Boundary for River Rch & Prof#=Elm 27,Reach-1,3
Up Type=0
Dn Type=3
Dn Slope=0.005
Boundary for River Rch & Prof#=Elm 27,Reach-1,4
Up Type=0
Dn Type=3
Dn Slope=0.005
Boundary for River Rch & Prof#=Elm 27,Reach-1,5
Up Type=0
Dn Type=3
Dn Slope=0.005
Boundary for River Rch & Prof#=Elm 27,Reach-1,6
Up Type=0
Dn Type=3
Dn Slope=0.005
Boundary for River Rch & Prof#=Elm 27,Reach-1,7
Up Type=0
Dn Type=3
Dn Slope=0.005

--- Elm 27.g01 (geometry) ---

Geom Title=Existing Conditions

River Reach=Elm 27,Reach-1
Reach XY= 26
      1504955.00      6782438.00      1504954.90      6782406.19
      1504951.40      6782389.49      1504910.95      6782340.25
      1504900.82      6782289.73      1504863.04      6782244.05
      1504855.36      6782222.73      1504854.51      6782162.96
      1504860.41      6782135.58      1504874.63      6782117.86
      1504938.54      6782054.75      1504951.46      6782036.53
      1504955.32      6782013.11      1504955.57      6781927.77
      1504951.56      6781889.25      1504928.96      6781860.81
      1504903.57      6781841.89      1504860.88      6781835.53
      1504848.64      6781829.97      1504818.22      6781801.67
      1504806.97      6781782.33      1504804.43      6781748.24
      1504805.65      6781696.01      1504806.88      6781643.79
      1504817.91      6781624.50      1504855.00      6781588.00

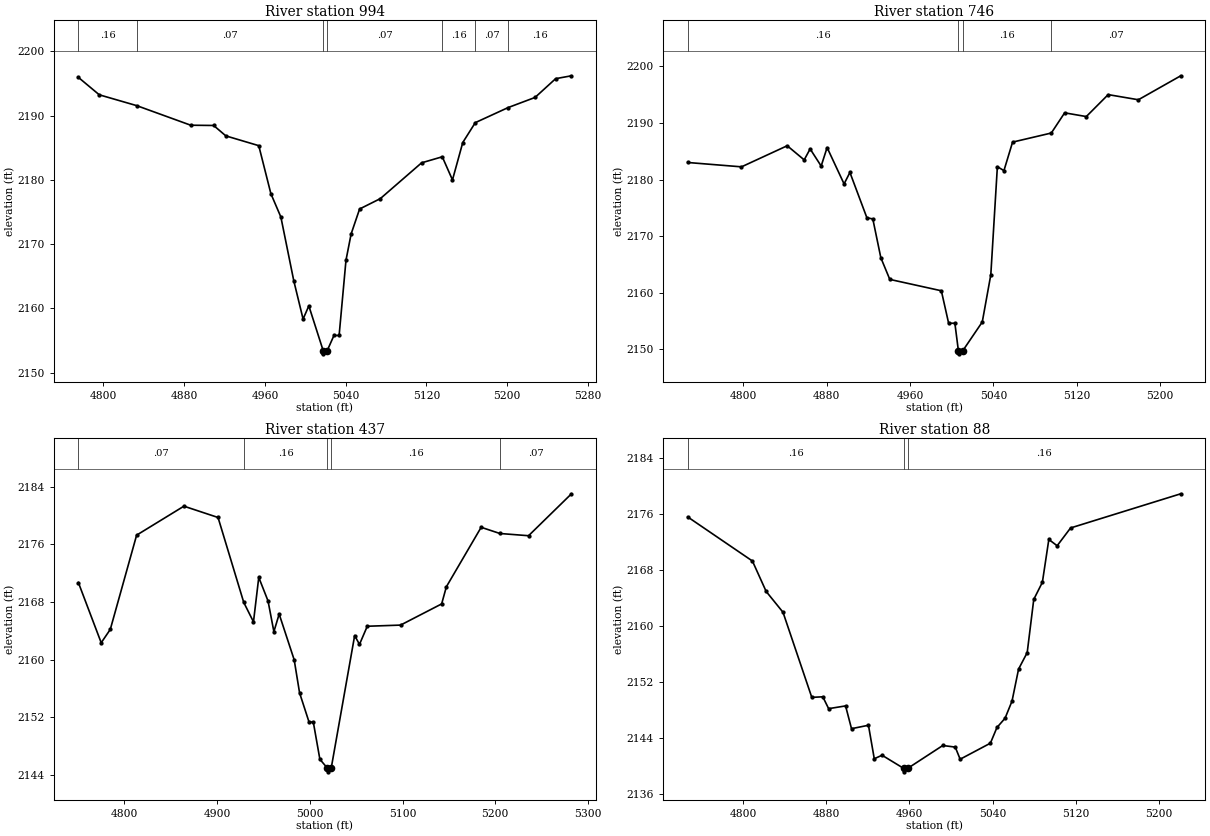
Type RM Length L Ch R = 1,994,248,248,248
BEGIN DESCRIPTION:
778
END DESCRIPTION:
XS GIS Cut Line= 3
      1505153.22      6782519.53      1504929.76      6782400.20
      1504699.66      6782448.78
#Sta/Elev= 30
  4775.2 2195.94  4795.9 2193.23  4833.1 2191.54  4886.5 2188.50  4909.2 2188.46
  4921.3 2186.84  4953.9 2185.32  4965.9 2177.85  4975.8 2174.22  4988.6 2164.29
  4997.8 2158.35  5003.5 2160.40  5017.7 2153.44  5018.0 2152.94  5021.7 2153.44
  5028.4 2155.80  5033.5 2155.80  5040.3 2167.50  5045.4 2171.59  5053.8 2175.47
  5074.3 2177.08  5115.2 2182.65  5135.7 2183.59  5145.8 2179.99  5156.0 2185.81
  5168.4 2188.90  5201.0 2191.25  5227.6 2192.82  5248.0 2195.74  5263.7 2196.19
#Mann=7,-1,0
  4775.2    0.16       0  4833.1    0.07       0  5017.7    0.07       0
  5021.7    0.07       0  5135.7    0.16       0  5168.4    0.07       0
  5201.0    0.16       0
Bank Sta=5017.7,5021.7
Exp/Cntr=0.3,0.1

Type RM Length L Ch R = 1,746,309,309,309
BEGIN DESCRIPTION:
780
END DESCRIPTION:
XS GIS Cut Line= 3
      1505078.66      6782315.76      1504855.22      6782196.44
      1504679.34      6782328.91
#Sta/Elev= 30
  4746.4 2183.02  4798.1 2182.25  4842.0 2185.98  4858.3 2183.48  4864.0 2185.42
  4874.6 2182.39  4880.3 2185.66  4896.6 2179.23  4902.2 2181.26  4918.5 2173.25
  4924.2 2173.04  4931.9 2166.18  4940.5 2162.35  4990.0 2160.34  4997.0 2154.60
  5003.0 2154.60  5006.4 2149.69  5006.7 2149.19  5010.4 2149.69  5029.3 2154.82
  5037.5 2163.17  5043.8 2182.28  5050.1 2181.58  5058.4 2186.62  5095.6 2188.23
  5108.4 2191.80  5129.2 2191.14  5150.2 2195.02  5179.2 2194.11  5219.9 2198.35
#Mann=4,-1,0
  4746.4    0.16       0  5006.4    0.07       0  5010.4    0.16       0
  5095.6    0.07       0
Bank Sta=5006.4,5010.4
Exp/Cntr=0.3,0.1

Type RM Length L Ch R = 1,437,349,349,349
BEGIN DESCRIPTION:
779
END DESCRIPTION:
XS GIS Cut Line= 3
      1505175.37      6782042.60      1504951.92      6781923.28
      1504679.73      6781981.64
#Sta/Elev= 30
  4750.5 2170.70  4775.1 2162.35  4784.9 2164.20  4813.3 2177.28  4864.3 2181.30
  4901.1 2179.73  4928.8 2167.95  4939.3 2165.25  4945.0 2171.42  4955.0 2168.15
  4961.3 2163.89  4967.0 2166.33  4983.2 2159.98  4989.0 2155.40  4999.2 2151.35
  5003.8 2151.35  5010.9 2146.18  5019.1 2144.94  5019.4 2144.44  5023.1 2144.94
  5048.4 2163.35  5053.6 2162.12  5062.0 2164.64  5097.9 2164.80  5142.2 2167.74
  5147.3 2170.12  5184.8 2178.37  5205.0 2177.51  5235.9 2177.20  5282.2 2183.02
#Mann=5,-1,0
  4750.5    0.07       0  4928.8    0.16       0  5019.1    0.07       0
  5023.1    0.16       0  5205.0    0.07       0
Bank Sta=5019.1,5023.1
Exp/Cntr=0.3,0.1

Type RM Length L Ch R = 1,88,0,0,0
BEGIN DESCRIPTION:
468
END DESCRIPTION:
XS GIS Cut Line= 3
      1505030.00      6781776.72      1504806.56      6781657.40
      1504630.03      6781790.36
#Sta/Elev= 30
  4746.7 2175.62  4809.0 2169.32  4822.2 2164.98  4838.4 2162.01  4866.1 2149.86
  4876.7 2149.94  4882.3 2148.25  4898.6 2148.64  4904.3 2145.39  4920.6 2145.88
  4926.2 2141.10  4933.7 2141.60  4954.4 2139.73  4954.7 2139.23  4958.4 2139.73
  4992.1 2142.99  5004.1 2142.76  5008.8 2141.03  5037.9 2143.32  5044.2 2145.56
  5052.0 2146.88  5058.7 2149.33  5065.0 2153.90  5073.3 2156.25  5079.6 2163.84
  5087.9 2166.29  5094.1 2172.40  5102.1 2171.50  5115.0 2174.04  5221.0 2178.92
#Mann=3,-1,0
  4746.7    0.16       0  4954.4    0.07       0  4958.4    0.16       0
Bank Sta=4954.4,4958.4
Exp/Cntr=0.3,0.1

Chan Stop Cuts=-1