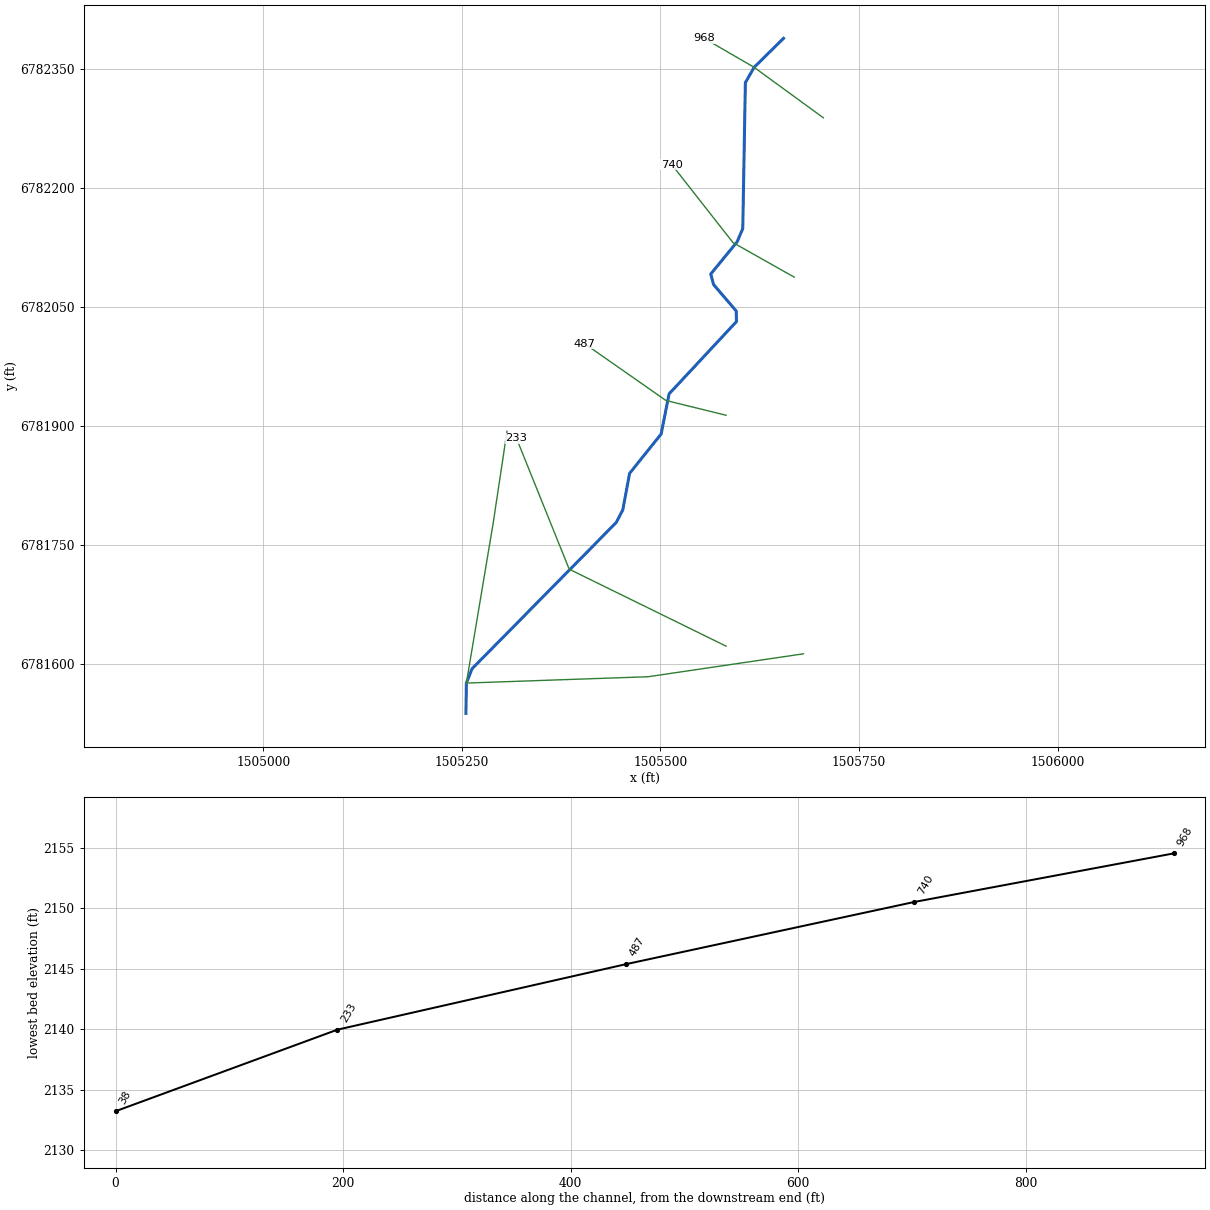
--- Elm 28.prj (project) ---

Proj Title=Elm 28 Base Level Engineering
Current Plan=p01
Default Exp/Contr=0.3,0.1
English Units
Geom File=g01
Flow File=f01
Plan File=p01
BEGIN DESCRIPTION:
Elm 28
END DESCRIPTION:

--- Elm 28.p01 (plan) ---

Plan Title=Multiple Run
Short Identifier=Multiple
Geom File=g01
Flow File=f01
Subcritical Flow
K Sum by GR= 0
Std Step Tol= 0.01
Critical Tol= 0.01
Num of Std Step Trials= 20
Max Error Tol= 0.3
Flow Tol Ratio= 0.001
Split Flow NTrial= 30
Split Flow Tol= 0.02
Split Flow Ratio= 0.02
Log Output Level= 0
Friction Slope Method= 1
Unsteady Friction Slope Method= 2
Unsteady Bridges Friction Slope Method= 1
Parabolic Critical Depth
Global Vel Dist=  1 , 1 , 1
Global Log Level= 0
CheckData=True
Encroach Param= -1, 0, 0, 0
BEGIN DESCRIPTION:
Multiple Run
END DESCRIPTION:

--- Elm 28.f01 (steady flow) ---

Flow Title=Multiple
Number of Profiles=7
Profile Names=10-year,25-year,50-year,1pct_min,100-year,1pct_plu,500-year
River Rch & RM= Elm 28,Reach-1,968
     106     142     171     129     207     285     305
Boundary for River Rch & Prof#=Elm 28,Reach-1,1
Up Type=0
Dn Type=3
Dn Slope=0.005
Boundary for River Rch & Prof#=Elm 28,Reach-1,2
Up Type=0
Dn Type=3
Dn Slope=0.005
Boundary for River Rch & Prof#=Elm 28,Reach-1,3
Up Type=0
Dn Type=3
Dn Slope=0.005
Boundary for River Rch & Prof#=Elm 28,Reach-1,4
Up Type=0
Dn Type=3
Dn Slope=0.005
Boundary for River Rch & Prof#=Elm 28,Reach-1,5
Up Type=0
Dn Type=3
Dn Slope=0.005
Boundary for River Rch & Prof#=Elm 28,Reach-1,6
Up Type=0
Dn Type=3
Dn Slope=0.005
Boundary for River Rch & Prof#=Elm 28,Reach-1,7
Up Type=0
Dn Type=3
Dn Slope=0.005

--- Elm 28.g01 (geometry) ---

Geom Title=Existing Conditions

River Reach=Elm 28,Reach-1
Reach XY= 21
      1505655.00      6782388.00      1505617.92      6782351.50
      1505606.89      6782332.22      1505605.26      6782240.32
      1505603.62      6782148.43      1505596.56      6782131.81
      1505563.29      6782091.21      1505566.85      6782077.94
      1505595.40      6782044.66      1505595.69      6782031.34
      1505553.27      6781985.82      1505510.86      6781940.30
      1505500.81      6781889.74      1505461.10      6781840.19
      1505452.50      6781794.04      1505444.24      6781778.32
      1505383.74      6781716.95      1505323.25      6781655.58
      1505262.76      6781594.21      1505255.59      6781576.16
      1505255.00      6781538.00

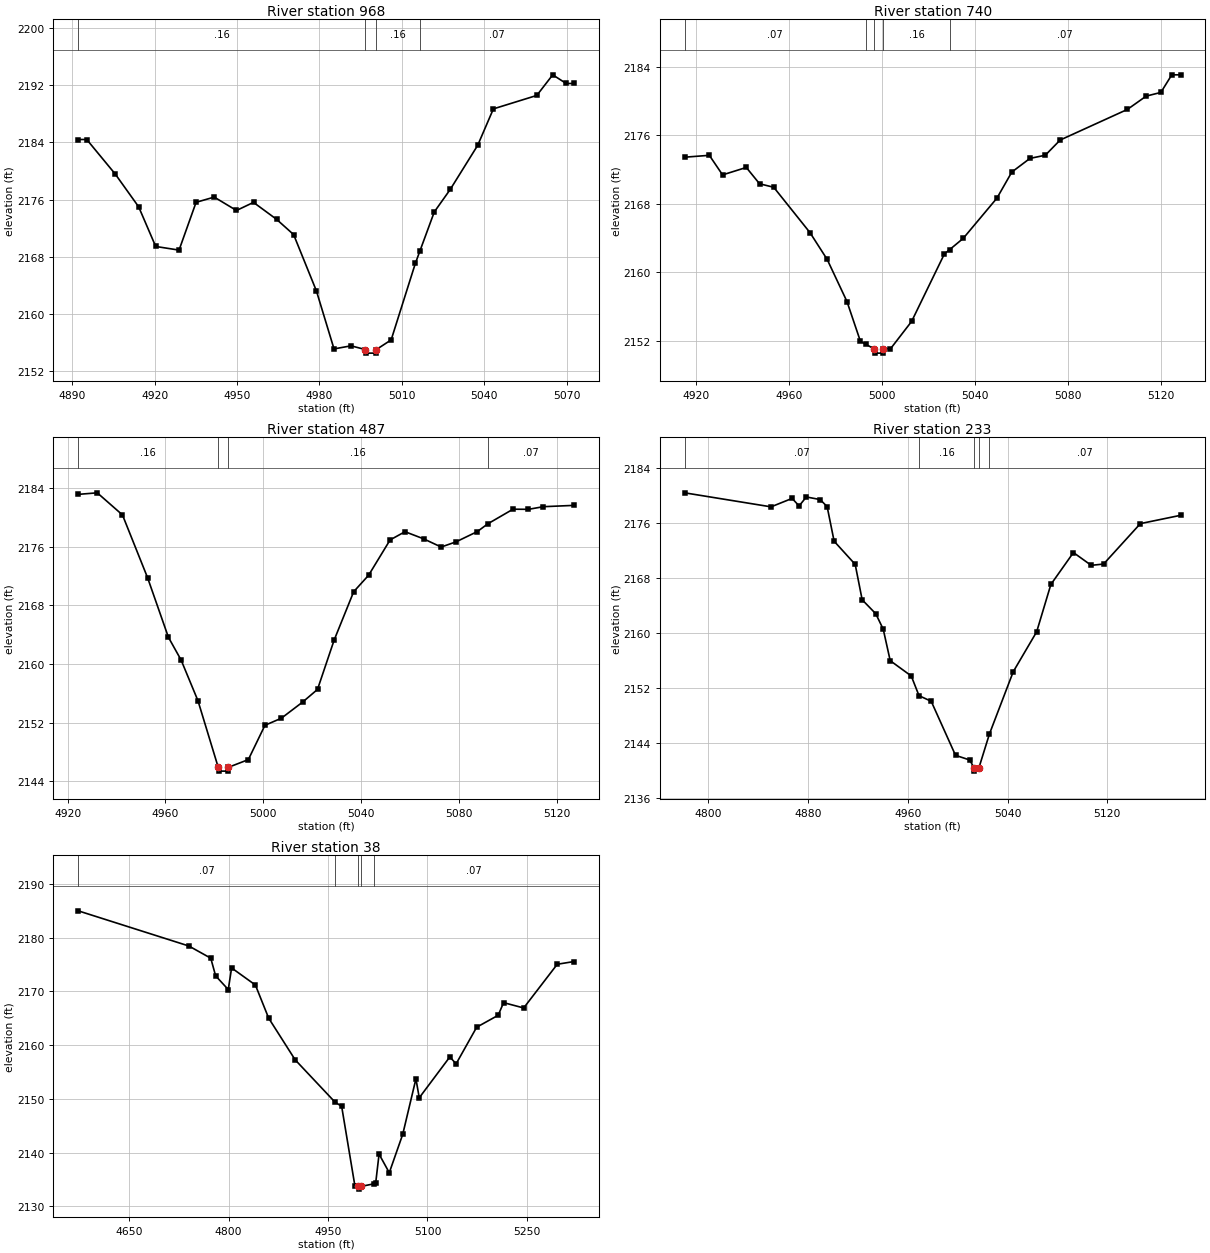
Type RM Length L Ch R = 1,968,228,228,228
BEGIN DESCRIPTION:
470
END DESCRIPTION:
XS GIS Cut Line= 3
      1505705.02      6782287.99      1505617.92      6782351.50
      1505555.03      6782387.98
#Sta/Elev= 30
  4892.2 2184.41  4895.3 2184.41  4905.7 2179.57  4914.2 2175.00  4920.4 2169.46
  4928.9 2168.95  4935.1 2175.63  4941.7 2176.36  4949.8 2174.49  4956.0 2175.62
  4964.4 2173.25  4970.6 2171.12  4978.9 2163.24  4985.3 2155.14  4991.5 2155.57
  4996.7 2155.05  4997.0 2154.55  5000.5 2154.55  5000.7 2155.05  5006.1 2156.40
  5014.9 2167.09  5016.5 2168.76  5021.8 2174.29  5027.6 2177.43  5037.6 2183.60
  5043.3 2188.69  5059.1 2190.57  5064.9 2193.45  5069.8 2192.24  5072.7 2192.24
#Mann=4,-1,0
  4892.2    0.16       0  4996.7    0.07       0  5000.7    0.16       0
  5016.5    0.07       0
Bank Sta=4996.7,5000.7
Exp/Cntr=0.3,0.1

Type RM Length L Ch R = 1,740,253,253,253
BEGIN DESCRIPTION:
777
END DESCRIPTION:
XS GIS Cut Line= 3
      1505668.36      6782087.31      1505591.31      6782130.81
      1505514.25      6782228.99
#Sta/Elev= 30
  4915.0 2173.46  4925.6 2173.68  4931.3 2171.39  4941.5 2172.26  4947.2 2170.35
  4953.3 2169.94  4968.9 2164.63  4976.3 2161.49  4984.8 2156.57  4990.6 2151.90
  4992.8 2151.58  4996.5 2151.03  4996.7 2150.53  5000.2 2150.53  5000.5 2151.03
  5003.5 2151.03  5012.6 2154.24  5026.7 2162.14  5028.9 2162.63  5034.8 2163.96
  5049.3 2168.67  5055.7 2171.72  5063.5 2173.32  5070.1 2173.69  5076.5 2175.47
  5105.4 2179.05  5113.5 2180.61  5119.8 2181.04  5124.5 2183.10  5128.3 2183.10
#Mann=5,-1,0
  4915.0    0.07       0  4992.8    0.16       0  4996.5    0.07       0
  5000.5    0.16       0  5028.9    0.07       0
Bank Sta=4996.5,5000.5
Exp/Cntr=0.3,0.1

Type RM Length L Ch R = 1,487,254,254,254
BEGIN DESCRIPTION:
776
END DESCRIPTION:
XS GIS Cut Line= 3
      1505582.62      6781913.38      1505506.82      6781932.02
      1505404.48      6782003.53
#Sta/Elev= 30
  4924.3 2183.12  4932.1 2183.33  4942.4 2180.32  4952.7 2171.74  4961.2 2163.64
  4966.4 2160.53  4973.3 2154.98  4981.6 2145.89  4981.9 2145.39  4985.4 2145.39
  4985.6 2145.89  4993.9 2146.96  5000.7 2151.64  5007.4 2152.60  5016.1 2154.80
  5022.2 2156.53  5029.0 2163.25  5037.0 2169.85  5043.1 2172.09  5051.9 2176.91
  5058.0 2178.03  5065.6 2177.06  5072.8 2175.94  5078.9 2176.65  5087.6 2178.05
  5091.9 2179.11  5102.2 2181.10  5108.5 2181.08  5114.6 2181.44  5127.2 2181.62
#Mann=4,-1,0
  4924.3    0.16       0  4981.6    0.07       0  4985.6    0.16       0
  5091.9    0.07       0
Bank Sta=4981.6,4985.6
Exp/Cntr=0.3,0.1

Type RM Length L Ch R = 1,233,195,195,195
BEGIN DESCRIPTION:
775
END DESCRIPTION:
XS GIS Cut Line= 3
      1505582.62      6781622.65      1505385.06      6781719.57
      1505318.59      6781884.53
#Sta/Elev= 30
  4780.9 2180.45  4850.2 2178.41  4867.1 2179.64  4872.7 2178.54  4878.5 2179.85
  4889.6 2179.47  4895.2 2178.44  4900.8 2173.41  4917.7 2170.04  4923.3 2164.89
  4934.2 2162.86  4940.2 2160.61  4945.8 2156.03  4962.7 2153.80  4968.9 2150.94
  4978.7 2150.12  4998.2 2142.26  5009.6 2141.58  5013.0 2140.46  5013.2 2139.96
  5017.0 2140.46  5025.4 2145.36  5044.5 2154.42  5063.3 2160.23  5074.7 2167.12
  5092.8 2171.76  5107.1 2169.90  5117.0 2170.09  5146.5 2175.97  5178.8 2177.18
#Mann=5,-1,0
  4780.9    0.07       0  4968.9    0.16       0  5013.0    0.07       0
  5017.0    0.16       0  5025.4    0.07       0
Bank Sta=5013,5017
Exp/Cntr=0.3,0.1

Type RM Length L Ch R = 1,38,0,0,0
BEGIN DESCRIPTION:
469
END DESCRIPTION:
XS GIS Cut Line= 5
      1505680.03      6781613.00      1505484.46      6781584.14
      1505255.59      6781576.16      1505289.40      6781777.96
      1505306.75      6781893.24
#Sta/Elev= 30
  4573.3 2184.98  4740.1 2178.44  4773.2 2176.17  4780.5 2172.89  4799.6 2170.33
  4804.6 2174.36  4840.5 2171.18  4860.5 2165.02  4900.5 2157.26  4960.2 2149.44
  4970.6 2148.60  4990.6 2133.78  4995.8 2133.71  4996.0 2133.21  4999.8 2133.71
  5018.8 2134.19  5021.9 2134.34  5027.0 2139.72  5042.4 2136.26  5062.7 2143.41
  5082.6 2153.73  5087.6 2150.20  5133.7 2157.80  5143.2 2156.52  5174.2 2163.33
  5206.6 2165.55  5214.8 2167.90  5245.1 2166.91  5295.7 2175.04  5321.2 2175.55
#Mann=5,-1,0
  4573.3    0.07       0  4960.2    0.16       0  4995.8    0.07       0
  4999.8    0.16       0  5018.8    0.07       0
Bank Sta=4995.8,4999.8
Exp/Cntr=0.3,0.1

Chan Stop Cuts=-1