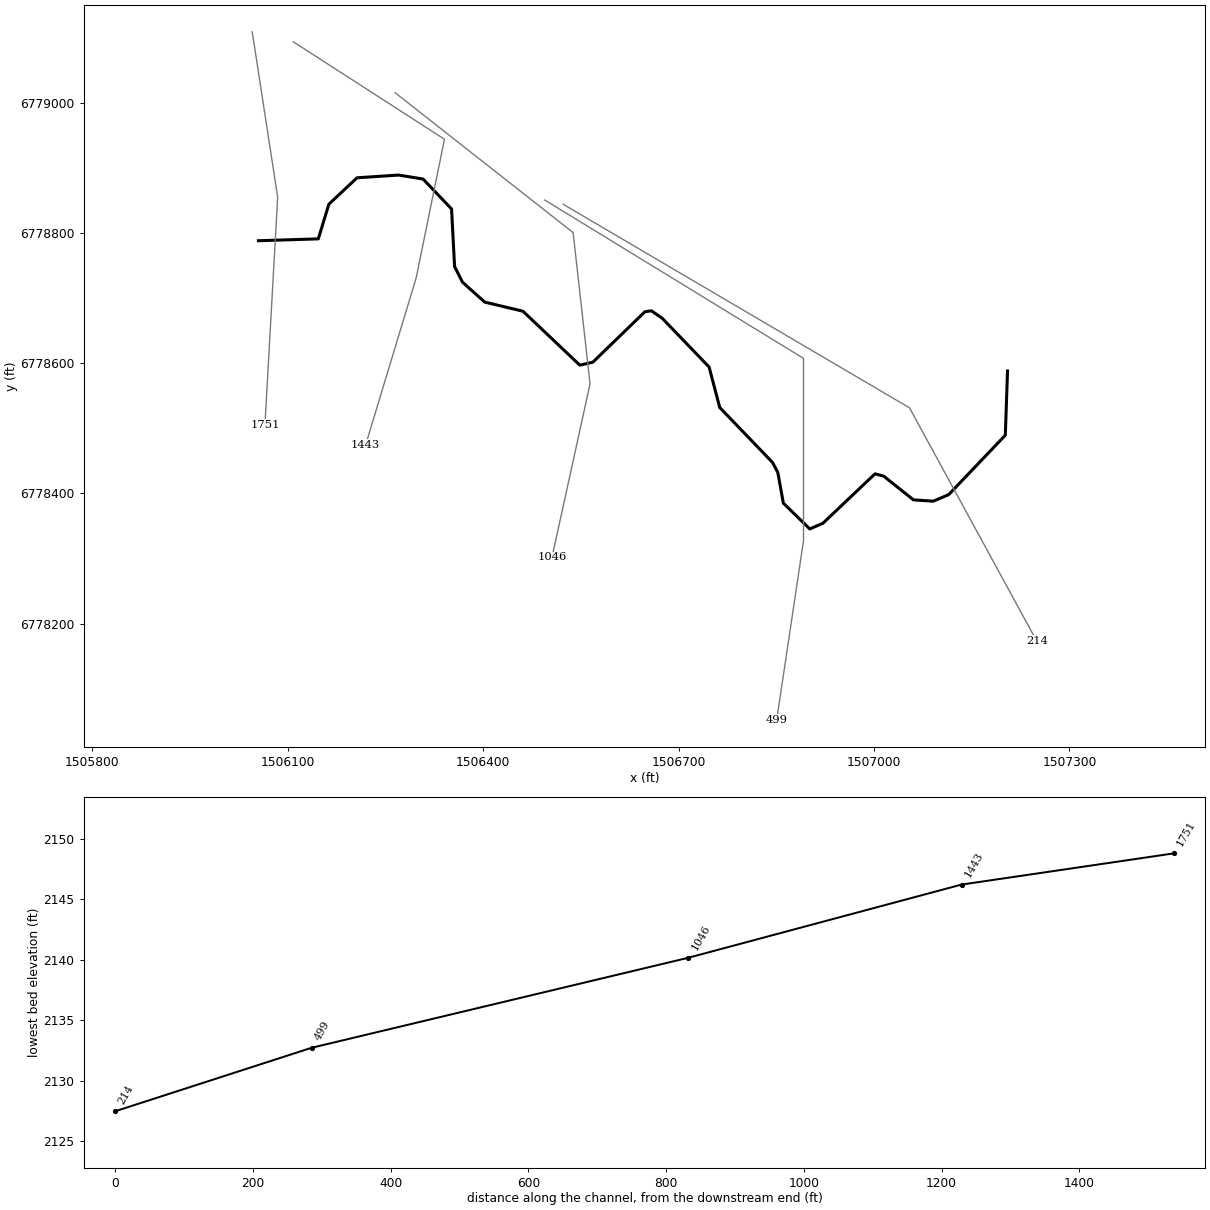
--- Elm 29.prj (project) ---

Proj Title=Elm 29 Base Level Engineering
Current Plan=p01
Default Exp/Contr=0.3,0.1
English Units
Geom File=g01
Flow File=f01
Plan File=p01
BEGIN DESCRIPTION:
Elm 29
END DESCRIPTION:

--- Elm 29.p01 (plan) ---

Plan Title=Multiple Run
Short Identifier=Multiple
Geom File=g01
Flow File=f01
Subcritical Flow
K Sum by GR= 0
Std Step Tol= 0.01
Critical Tol= 0.01
Num of Std Step Trials= 20
Max Error Tol= 0.3
Flow Tol Ratio= 0.001
Split Flow NTrial= 30
Split Flow Tol= 0.02
Split Flow Ratio= 0.02
Log Output Level= 0
Friction Slope Method= 1
Unsteady Friction Slope Method= 2
Unsteady Bridges Friction Slope Method= 1
Parabolic Critical Depth
Global Vel Dist=  1 , 1 , 1
Global Log Level= 0
CheckData=True
Encroach Param= -1, 0, 0, 0
BEGIN DESCRIPTION:
Multiple Run
END DESCRIPTION:

--- Elm 29.f01 (steady flow) ---

Flow Title=Multiple
Number of Profiles=7
Profile Names=10-year,25-year,50-year,1pct_min,100-year,1pct_plu,500-year
River Rch & RM= Elm 29,Reach-1,1751
     343     490     615     479     768    1060    1210
Boundary for River Rch & Prof#=Elm 29,Reach-1,1
Up Type=0
Dn Type=3
Dn Slope=0.005
Boundary for River Rch & Prof#=Elm 29,Reach-1,2
Up Type=0
Dn Type=3
Dn Slope=0.005
Boundary for River Rch & Prof#=Elm 29,Reach-1,3
Up Type=0
Dn Type=3
Dn Slope=0.005
Boundary for River Rch & Prof#=Elm 29,Reach-1,4
Up Type=0
Dn Type=3
Dn Slope=0.005
Boundary for River Rch & Prof#=Elm 29,Reach-1,5
Up Type=0
Dn Type=3
Dn Slope=0.005
Boundary for River Rch & Prof#=Elm 29,Reach-1,6
Up Type=0
Dn Type=3
Dn Slope=0.005
Boundary for River Rch & Prof#=Elm 29,Reach-1,7
Up Type=0
Dn Type=3
Dn Slope=0.005

--- Elm 29.g01 (geometry) ---

Geom Title=Existing Conditions

River Reach=Elm 29,Reach-1
Reach XY= 30
      1506055.00      6778788.00      1506146.88      6778790.86
      1506163.12      6778844.08      1506206.30      6778884.61
      1506270.13      6778888.82      1506307.71      6778882.72
      1506351.48      6778836.75      1506356.11      6778748.34
      1506368.26      6778724.35      1506402.43      6778693.74
      1506461.03      6778679.79      1506548.34      6778596.99
      1506568.34      6778601.47      1506648.34      6778679.01
      1506658.35      6778680.40      1506675.04      6778668.80
      1506746.84      6778594.09      1506763.18      6778531.96
      1506844.20      6778447.64      1506852.35      6778432.28
      1506860.86      6778385.14      1506901.42      6778345.50
      1506921.58      6778354.23      1507001.59      6778430.15
      1507014.87      6778426.60      1507060.64      6778390.11
      1507090.94      6778388.15      1507114.70      6778398.19
      1507201.62      6778489.39      1507205.00      6778588.00

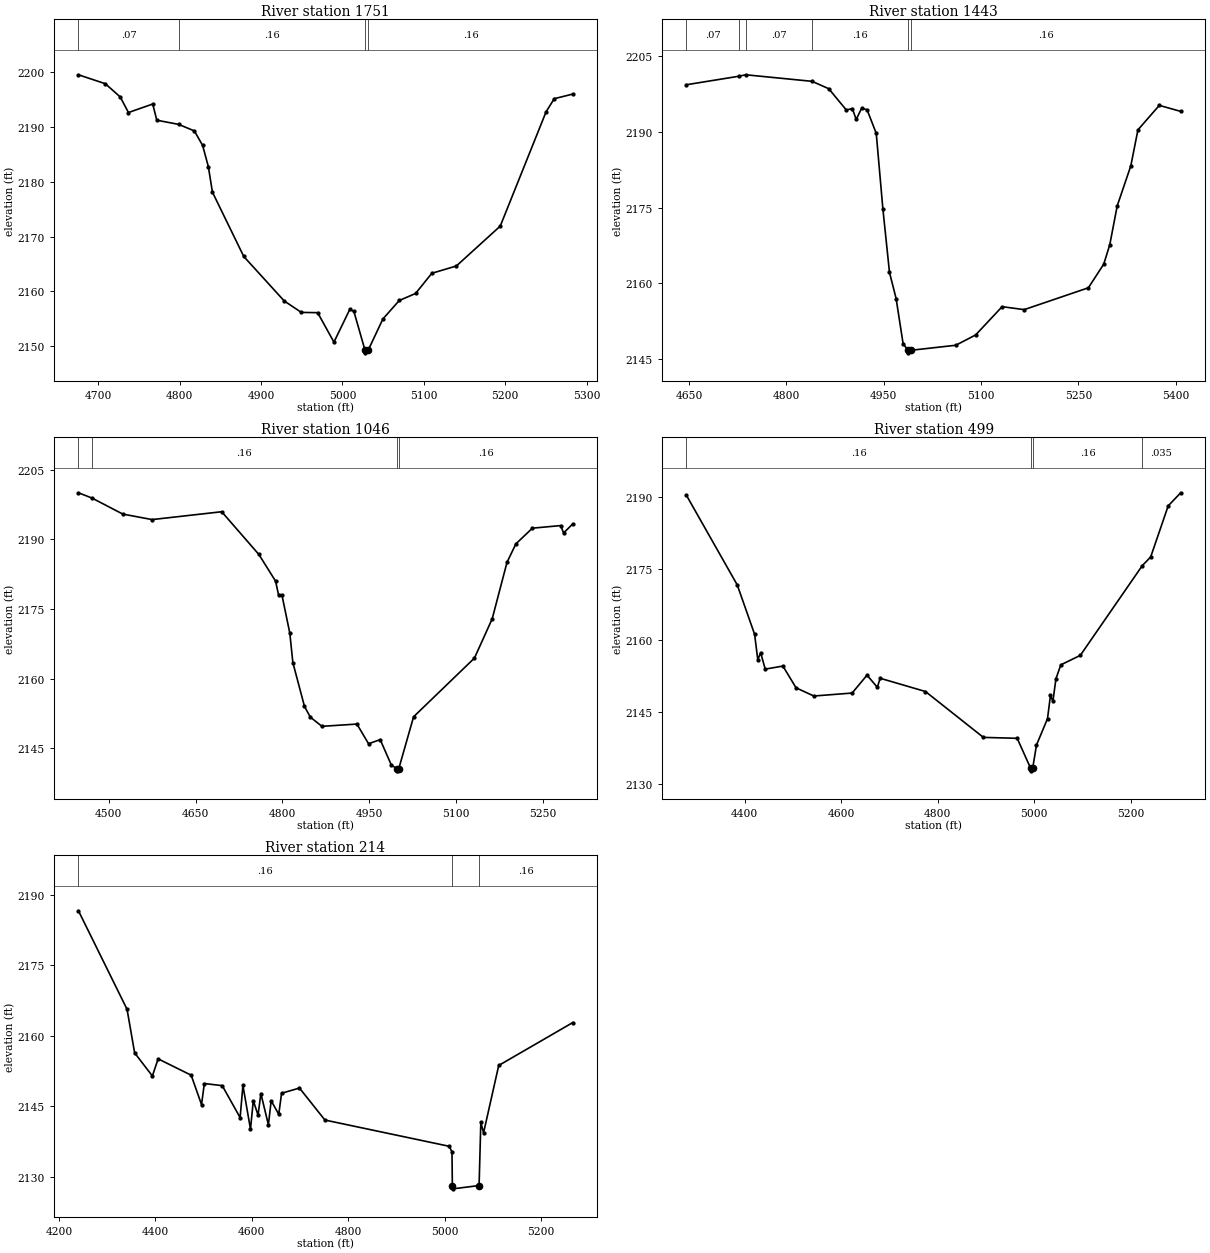
Type RM Length L Ch R = 1,1751,308,308,308
BEGIN DESCRIPTION:
elmc299
END DESCRIPTION:
XS GIS Cut Line= 3
      1506045.45      6779108.67      1506084.51      6778854.79
      1506064.98      6778505.40
#Sta/Elev= 30
  4675.9 2199.48  4708.9 2197.85  4727.2 2195.44  4737.3 2192.60  4767.1 2194.15
  4772.1 2191.20  4798.9 2190.44  4818.2 2189.25  4828.3 2186.63  4835.4 2182.74
  4840.4 2178.09  4878.9 2166.36  4928.6 2158.25  4949.6 2156.17  4969.6 2156.12
  4989.6 2150.75  5009.1 2156.73  5014.1 2156.34  5027.7 2149.30  5028.0 2148.80
  5031.7 2149.30  5049.7 2154.97  5069.8 2158.34  5089.8 2159.62  5109.8 2163.30
  5139.9 2164.63  5193.8 2171.90  5250.1 2192.74  5260.1 2195.12  5282.7 2195.96
#Mann=4,-1,0
  4675.9    0.07       0  4798.9    0.16       0  5027.7    0.07       0
  5031.7    0.16       0
Bank Sta=5027.7,5031.7
Exp/Cntr=0.3,0.1

Type RM Length L Ch R = 1,1443,397,397,397
BEGIN DESCRIPTION:
elmc298
END DESCRIPTION:
XS GIS Cut Line= 4
      1506108.38      6779093.50      1506340.58      6778943.77
      1506297.18      6778731.09      1506219.54      6778474.43
#Sta/Elev= 30
  4646.1 2199.32  4726.3 2200.99  4737.4 2201.29  4839.7 2199.99  4865.3 2198.53
  4892.4 2194.31  4901.6 2194.61  4907.6 2192.44  4915.8 2194.62  4924.3 2194.38
  4938.5 2189.69  4948.7 2174.74  4958.9 2162.14  4969.1 2156.97  4979.9 2148.02
  4987.5 2146.72  4987.8 2146.22  4991.5 2146.72  5061.0 2147.72  5091.6 2149.76
  5132.4 2155.36  5166.5 2154.78  5265.3 2159.10  5289.0 2163.78  5298.3 2167.63
  5309.8 2175.34  5330.7 2183.24  5341.7 2190.38  5374.6 2195.23  5407.6 2194.04
#Mann=6,-1,0
  4646.1    0.07       0  4726.3    0.16       0  4737.4    0.07       0
  4839.7    0.16       0  4987.5    0.07       0  4991.5    0.16       0
Bank Sta=4987.5,4991.5
Exp/Cntr=0.3,0.1

Type RM Length L Ch R = 1,1046,547,547,547
BEGIN DESCRIPTION:
elmc297
END DESCRIPTION:
XS GIS Cut Line= 4
      1506264.66      6779015.35      1506538.07      6778800.54
      1506564.11      6778568.33      1506505.70      6778302.23
#Sta/Elev= 30
  4447.6 2200.02  4470.9 2198.89  4524.3 2195.43  4574.9 2194.25  4695.1 2195.94
  4759.3 2186.74  4788.2 2180.99  4793.3 2178.03  4799.1 2178.03  4812.8 2169.78
  4818.0 2163.48  4838.1 2154.03  4848.2 2151.72  4868.3 2149.74  4928.7 2150.23
  4948.8 2145.99  4968.9 2146.88  4988.1 2141.42  4997.1 2140.66  4997.4 2140.16
  5001.1 2140.66  5026.6 2151.80  5131.7 2164.43  5162.4 2172.89  5188.0 2185.05
  5203.3 2189.02  5231.8 2192.40  5280.7 2192.96  5285.8 2191.37  5301.4 2193.30
#Mann=4,-1,0
  4447.6    0.07       0  4470.9    0.16       0  4997.1    0.07       0
  5001.1    0.16       0
Bank Sta=4997.1,5001.1
Exp/Cntr=0.3,0.1

Type RM Length L Ch R = 1,499,285,285,285
BEGIN DESCRIPTION:
elmc296
END DESCRIPTION:
XS GIS Cut Line= 4
      1506494.63      6778850.47      1506891.80      6778607.39
      1506891.80      6778327.45      1506850.65      6778052.41
#Sta/Elev= 30
  4279.5 2190.28  4384.6 2171.58  4420.6 2161.26  4427.2 2155.93  4433.1 2157.40
  4442.6 2153.97  4479.2 2154.61  4506.5 2150.06  4543.3 2148.35  4622.6 2148.97
  4653.5 2152.71  4674.8 2150.17  4680.7 2152.06  4774.5 2149.29  4894.5 2139.70
  4964.5 2139.51  4992.5 2133.21  4992.8 2132.71  4996.5 2133.21  5004.5 2138.11
  5027.3 2143.62  5033.4 2148.46  5038.5 2147.24  5044.8 2151.98  5054.9 2154.86
  5095.3 2156.85  5223.6 2175.60  5241.0 2177.41  5277.3 2188.10  5303.2 2190.83
#Mann=4,-1,0
  4279.5    0.16       0  4992.5    0.07       0  4996.5    0.16       0
  5223.6   0.035       0
Bank Sta=4992.5,4996.5
Exp/Cntr=0.3,0.1

Type RM Length L Ch R = 1,214,0,0,0
BEGIN DESCRIPTION:
elmc295
END DESCRIPTION:
XS GIS Cut Line= 3
      1506522.83      6778843.96      1507054.56      6778531.44
      1507249.85      6778173.41
#Sta/Elev= 30
  4240.6 2186.55  4341.4 2165.61  4357.1 2156.35  4393.9 2151.44  4405.8 2155.08
  4474.3 2151.61  4495.8 2145.36  4501.6 2149.84  4538.7 2149.39  4575.8 2142.60
  4581.6 2149.43  4597.3 2140.13  4603.1 2146.19  4613.0 2143.12  4618.8 2147.72
  4634.4 2141.08  4640.2 2146.17  4655.9 2143.30  4661.7 2147.77  4698.8 2148.88
  4751.6 2142.08  5009.3 2136.50  5015.0 2135.30  5015.8 2128.16  5017.0 2127.46
  5071.2 2128.16  5074.8 2141.59  5080.5 2139.37  5111.9 2153.68  5265.2 2162.78
#Mann=3,-1,0
  4240.6    0.16       0  5015.8    0.07       0  5071.2    0.16       0
Bank Sta=5015.8,5071.2
Exp/Cntr=0.3,0.1

Chan Stop Cuts=-1