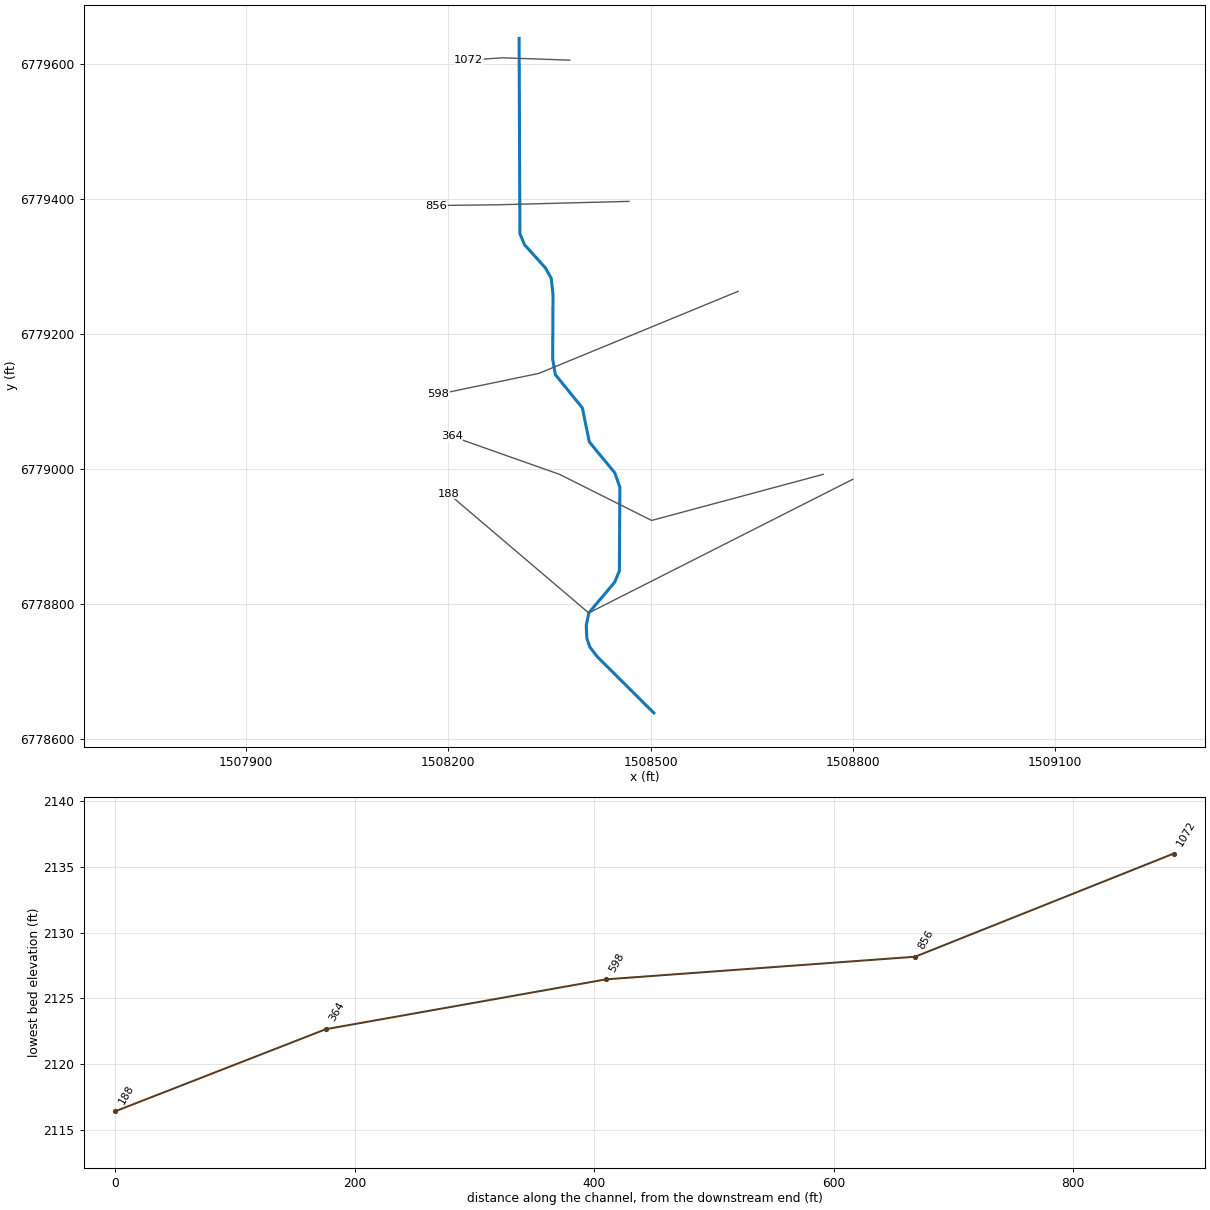
--- Elm 30.prj (project) ---

Proj Title=Elm 30 Base Level Engineering
Current Plan=p01
Default Exp/Contr=0.3,0.1
English Units
Geom File=g01
Flow File=f01
Plan File=p01
BEGIN DESCRIPTION:
Elm 30
END DESCRIPTION:

--- Elm 30.p01 (plan) ---

Plan Title=Multiple Run
Short Identifier=Multiple
Geom File=g01
Flow File=f01
Subcritical Flow
K Sum by GR= 0
Std Step Tol= 0.01
Critical Tol= 0.01
Num of Std Step Trials= 20
Max Error Tol= 0.3
Flow Tol Ratio= 0.001
Split Flow NTrial= 30
Split Flow Tol= 0.02
Split Flow Ratio= 0.02
Log Output Level= 0
Friction Slope Method= 1
Unsteady Friction Slope Method= 2
Unsteady Bridges Friction Slope Method= 1
Parabolic Critical Depth
Global Vel Dist=  1 , 1 , 1
Global Log Level= 0
CheckData=True
Encroach Param= -1, 0, 0, 0
BEGIN DESCRIPTION:
Multiple Run
END DESCRIPTION:

--- Elm 30.f01 (steady flow) ---

Flow Title=Multiple
Number of Profiles=7
Profile Names=10-year,25-year,50-year,1pct_min,100-year,1pct_plu,500-year
River Rch & RM= Elm 30,Reach-1,1072
     126     170     205     154     247     339     362
Boundary for River Rch & Prof#=Elm 30,Reach-1,1
Up Type=0
Dn Type=3
Dn Slope=0.005
Boundary for River Rch & Prof#=Elm 30,Reach-1,2
Up Type=0
Dn Type=3
Dn Slope=0.005
Boundary for River Rch & Prof#=Elm 30,Reach-1,3
Up Type=0
Dn Type=3
Dn Slope=0.005
Boundary for River Rch & Prof#=Elm 30,Reach-1,4
Up Type=0
Dn Type=3
Dn Slope=0.005
Boundary for River Rch & Prof#=Elm 30,Reach-1,5
Up Type=0
Dn Type=3
Dn Slope=0.005
Boundary for River Rch & Prof#=Elm 30,Reach-1,6
Up Type=0
Dn Type=3
Dn Slope=0.005
Boundary for River Rch & Prof#=Elm 30,Reach-1,7
Up Type=0
Dn Type=3
Dn Slope=0.005

--- Elm 30.g01 (geometry) ---

Geom Title=Existing Conditions

River Reach=Elm 30,Reach-1
Reach XY= 24
      1508305.00      6779638.00      1508305.41      6779541.50
      1508305.81      6779445.00      1508306.22      6779348.50
      1508313.14      6779331.94      1508344.14      6779297.64
      1508352.73      6779282.06      1508355.32      6779258.13
      1508354.81      6779162.92      1508358.76      6779139.56
      1508398.88      6779090.18      1508409.19      6779039.74
      1508446.91      6778994.07      1508454.51      6778972.78
      1508454.14      6778910.64      1508453.77      6778848.50
      1508446.82      6778831.93      1508408.34      6778786.26
      1508404.62      6778767.80      1508405.55      6778748.62
      1508410.00      6778735.68      1508421.09      6778721.29
      1508463.05      6778679.64      1508505.00      6778638.00

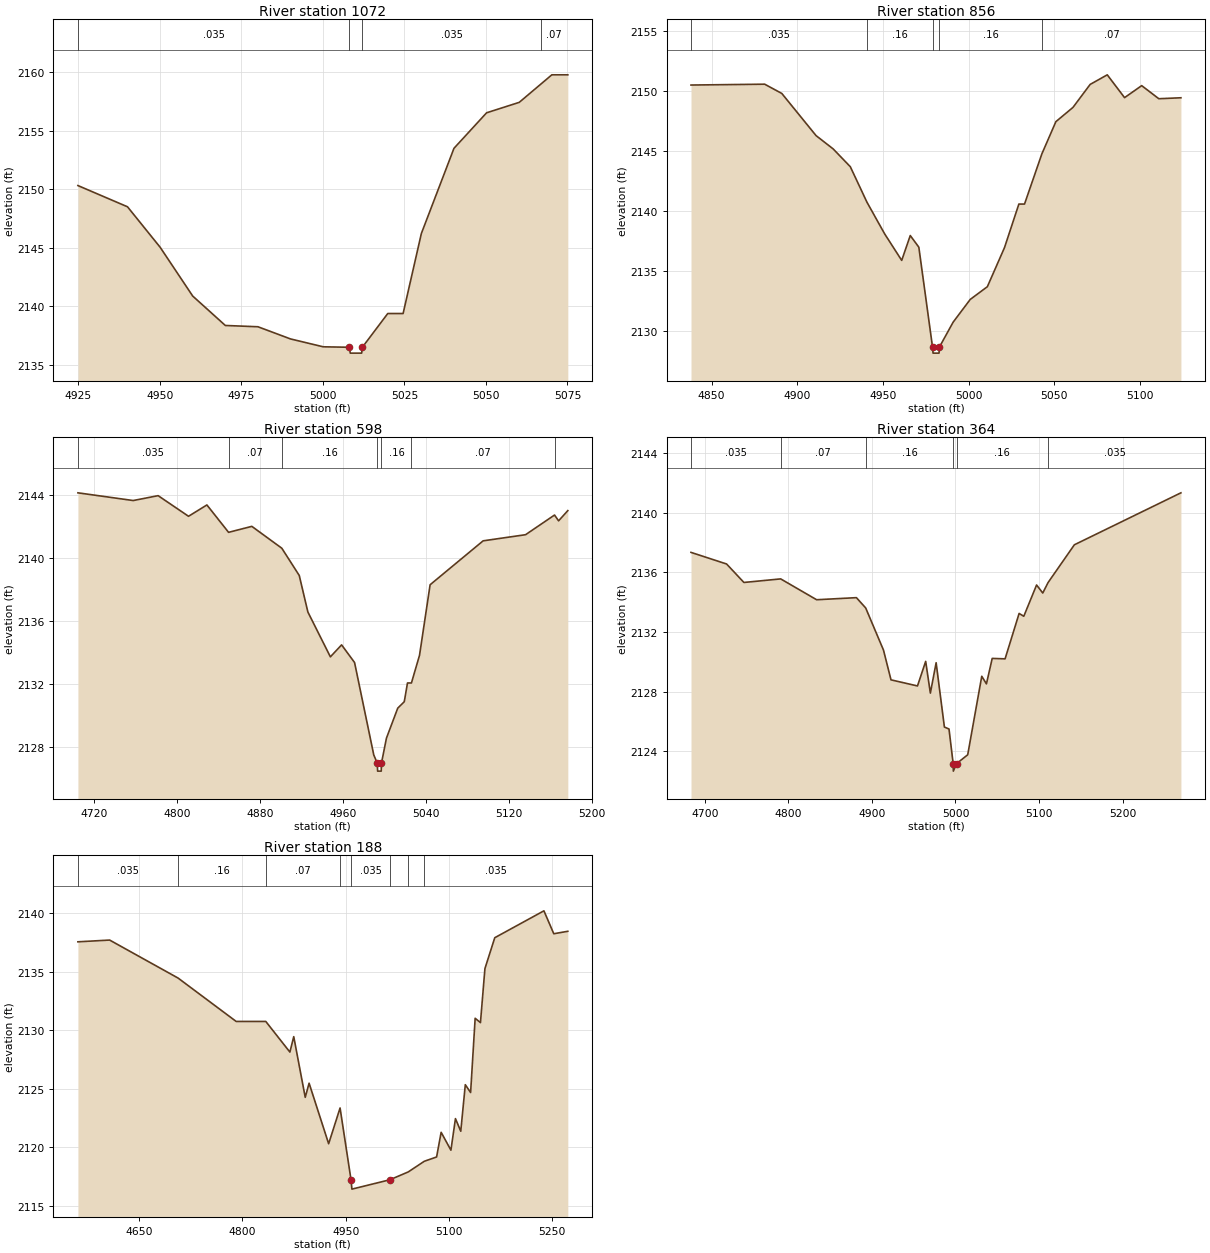
Type RM Length L Ch R = 1,1072,216,216,216
BEGIN DESCRIPTION:
464
END DESCRIPTION:
XS GIS Cut Line= 3
      1508380.18      6779605.63      1508280.54      6779609.14
      1508230.16      6779605.64
#Sta/Elev= 21
  4924.9 2150.32  4940.1 2148.51  4950.1 2145.06  4960.1 2140.89  4970.1 2138.38
  4980.1 2138.27  4990.1 2137.23  5000.1 2136.56  5008.1 2136.52  5008.4 2136.02
  5011.9 2136.02  5012.1 2136.52  5019.9 2139.40  5024.6 2139.40  5030.2 2146.23
  5040.2 2153.50  5050.2 2156.53  5060.2 2157.42  5066.8 2158.97  5070.2 2159.77
  5075.1 2159.77
#Mann=4,-1,0
  4924.9   0.035       0  5008.1   0.035       0  5012.1   0.035       0
  5066.8    0.07       0
Bank Sta=5008.1,5012.1
Exp/Cntr=0.3,0.1

Type RM Length L Ch R = 1,856,258,258,258
BEGIN DESCRIPTION:
783
END DESCRIPTION:
XS GIS Cut Line= 3
      1508467.98      6779396.32      1508273.30      6779391.26
      1508182.05      6779390.17
#Sta/Elev= 30
  4838.0 2150.49  4881.0 2150.56  4891.0 2149.79  4911.0 2146.28  4921.0 2145.17
  4931.0 2143.69  4940.7 2140.74  4951.0 2138.11  4961.0 2135.89  4966.0 2137.96
  4971.0 2136.99  4979.0 2128.67  4979.3 2128.17  4982.8 2128.17  4983.0 2128.67
  4991.0 2130.74  5001.0 2132.64  5011.0 2133.70  5021.0 2136.95  5029.4 2140.58
  5032.7 2140.58  5042.8 2144.75  5051.0 2147.44  5061.0 2148.63  5071.0 2150.54
  5081.0 2151.34  5091.1 2149.44  5101.1 2150.44  5111.1 2149.35  5124.0 2149.43
#Mann=5,-1,0
  4838.0   0.035       0  4940.7    0.16       0  4979.0    0.07       0
  4983.0    0.16       0  5042.8    0.07       0
Bank Sta=4979,4983
Exp/Cntr=0.3,0.1

Type RM Length L Ch R = 1,598,234,234,234
BEGIN DESCRIPTION:
782
END DESCRIPTION:
XS GIS Cut Line= 3
      1508629.98      6779262.99      1508334.16      6779141.31
      1508185.10      6779110.40
#Sta/Elev= 30
  4704.7 2144.13  4758.0 2143.64  4782.0 2143.95  4811.3 2142.64  4829.0 2143.36
  4849.9 2141.62  4872.3 2142.00  4901.2 2140.61  4918.0 2138.88  4926.3 2136.56
  4948.0 2133.71  4958.8 2134.47  4971.3 2133.35  4989.8 2127.48  4993.2 2126.95
  4993.5 2126.45  4997.0 2126.45  4997.2 2126.95  5002.0 2128.54  5012.9 2130.45
  5019.2 2130.86  5022.3 2132.05  5026.1 2132.05  5033.9 2133.81  5044.1 2138.29
  5095.2 2141.08  5136.1 2141.47  5164.0 2142.72  5167.9 2142.35  5176.8 2143.00
#Mann=7,-1,0
  4704.7   0.035       0  4849.9    0.07       0  4901.2    0.16       0
  4993.2    0.07       0  4997.2    0.16       0  5026.1    0.07       0
  5164.0   0.035       0
Bank Sta=4993.2,4997.2
Exp/Cntr=0.3,0.1

Type RM Length L Ch R = 1,364,176,176,176
BEGIN DESCRIPTION:
846
END DESCRIPTION:
XS GIS Cut Line= 4
      1508756.16      6778991.71      1508501.67      6778923.37
      1508365.01      6778991.70      1508204.79      6779048.25
#Sta/Elev= 30
  4683.6 2137.35  4726.2 2136.57  4746.9 2135.33  4790.9 2135.57  4833.9 2134.17
  4881.5 2134.31  4892.6 2133.62  4913.9 2130.79  4922.9 2128.79  4954.6 2128.38
  4964.4 2130.03  4970.0 2127.90  4976.9 2129.94  4986.8 2125.62  4992.3 2125.49
  4997.3 2123.16  4997.5 2122.66  5001.3 2123.16  5014.7 2123.76  5031.5 2129.03
  5037.1 2128.52  5044.0 2130.23  5059.4 2130.20  5076.2 2133.25  5081.8 2133.06
  5097.1 2135.16  5104.5 2134.62  5110.8 2135.32  5142.3 2137.86  5269.8 2141.35
#Mann=6,-1,0
  4683.6   0.035       0  4790.9    0.07       0  4892.6    0.16       0
  4997.3    0.07       0  5001.3    0.16       0  5110.8   0.035       0
Bank Sta=4997.3,5001.3
Exp/Cntr=0.3,0.1

Type RM Length L Ch R = 1,188,0,0,0
BEGIN DESCRIPTION:
781
END DESCRIPTION:
XS GIS Cut Line= 3
      1508799.99      6778984.34      1508408.34      6778786.26
      1508200.52      6778962.82
#Sta/Elev= 30
  4561.1 2137.56  4607.2 2137.71  4706.6 2134.46  4791.0 2130.75  4834.0 2130.75
  4869.0 2128.13  4874.6 2129.45  4891.3 2124.26  4896.9 2125.47  4925.3 2120.29
  4941.9 2123.35  4957.8 2117.21  4959.1 2116.41  5014.2 2117.21  5040.9 2117.88
  5064.2 2118.79  5082.1 2119.16  5088.7 2121.27  5102.9 2119.74  5109.5 2122.44
  5117.2 2121.36  5123.8 2125.34  5131.5 2124.67  5138.1 2131.02  5145.8 2130.65
  5152.3 2135.27  5166.6 2137.91  5238.0 2140.21  5252.3 2138.25  5272.7 2138.46
#Mann=8,-1,0
  4561.1   0.035       0  4706.6    0.16       0  4834.0    0.07       0
  4941.9   0.035       0  4957.8   0.035       0  5014.2   0.035       0
  5040.9    0.16       0  5064.2   0.035       0
Bank Sta=4957.8,5014.2
Exp/Cntr=0.3,0.1

Chan Stop Cuts=-1