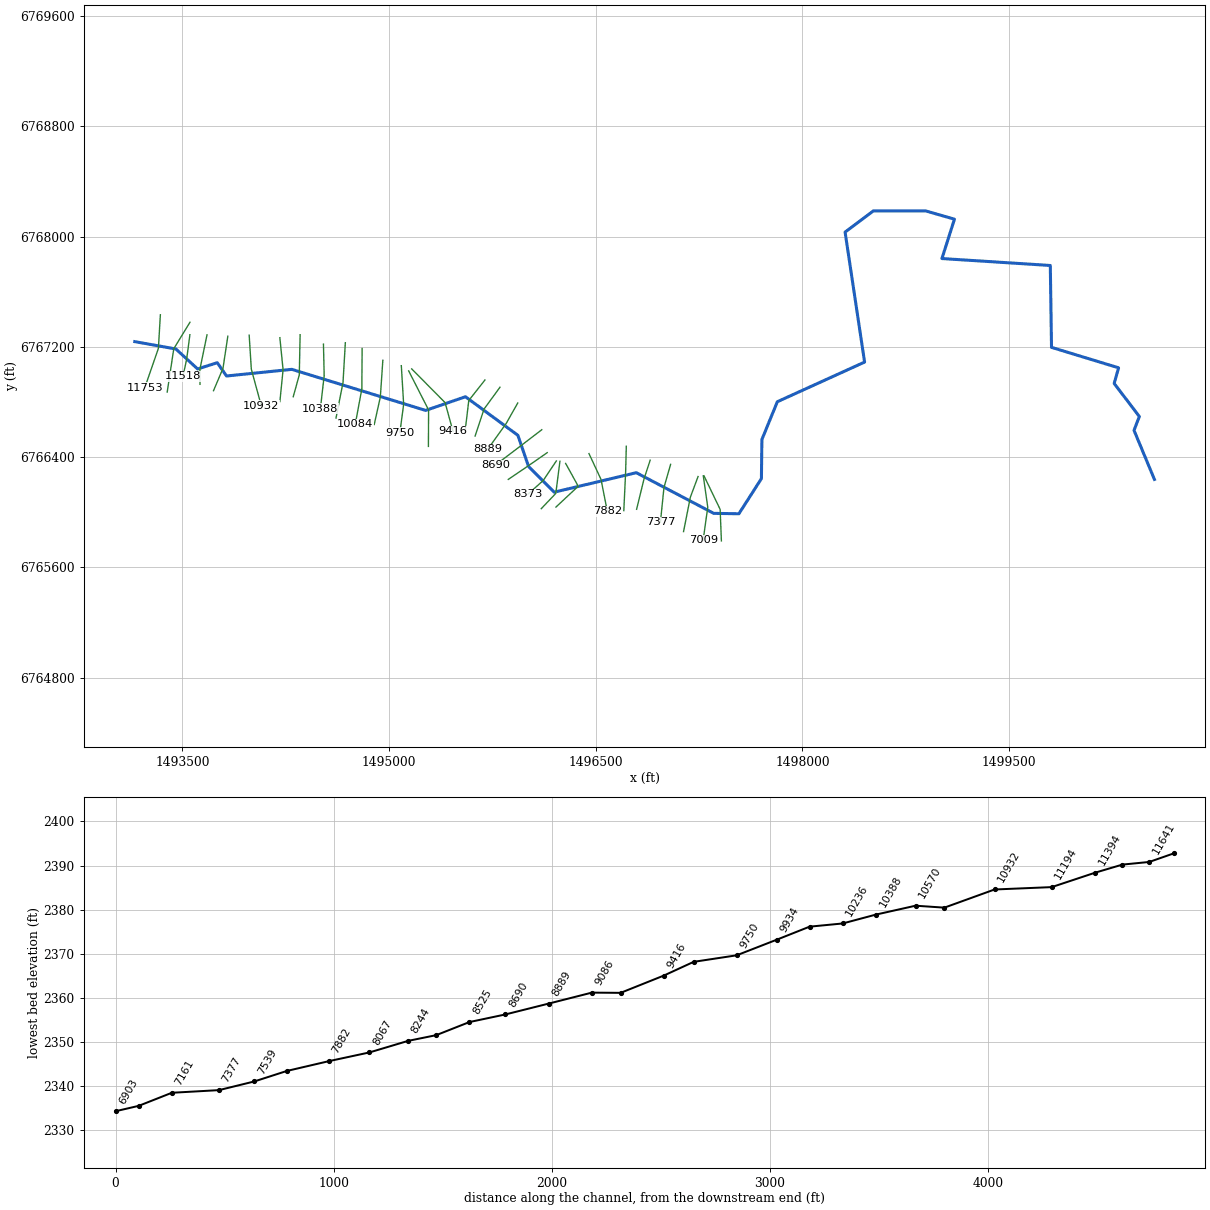
--- Elm 31.prj (project) ---

Proj Title=Elm 31 Base Level Engineering
Current Plan=p01
Default Exp/Contr=0.3,0.1
English Units
Geom File=g01
Flow File=f01
Plan File=p01
BEGIN DESCRIPTION:
Elm 31
END DESCRIPTION:

--- Elm 31.p01 (plan) ---

Plan Title=Multiple Run
Short Identifier=Multiple
Geom File=g01
Flow File=f01
Subcritical Flow
K Sum by GR= 0
Std Step Tol= 0.01
Critical Tol= 0.01
Num of Std Step Trials= 20
Max Error Tol= 0.3
Flow Tol Ratio= 0.001
Split Flow NTrial= 30
Split Flow Tol= 0.02
Split Flow Ratio= 0.02
Log Output Level= 0
Friction Slope Method= 1
Unsteady Friction Slope Method= 2
Unsteady Bridges Friction Slope Method= 1
Parabolic Critical Depth
Global Vel Dist=  1 , 1 , 1
Global Log Level= 0
CheckData=True
Encroach Param= -1, 0, 0, 0
BEGIN DESCRIPTION:
Multiple Run
END DESCRIPTION:

--- Elm 31.f01 (steady flow) ---

Flow Title=Multiple
Number of Profiles=7
Profile Names=10-year,25-year,50-year,1pct_min,100-year,1pct_plu,500-year
River Rch & RM= Elm 31,Reach-1,11753
     190     260     316     238     382     526     565
River Rch & RM= Elm 31,Reach-1,9218
     330     467     582     450     721     991    1120
River Rch & RM= Elm 31,Reach-1,7882
     421     605     761     593     951    1310    1500
River Rch & RM= Elm 31,Reach-1,3901
     510     739     937     735    1180    1620    1880
Boundary for River Rch & Prof#=Elm 31,Reach-1,1
Up Type=0
Dn Type=3
Dn Slope=0.005
Boundary for River Rch & Prof#=Elm 31,Reach-1,2
Up Type=0
Dn Type=3
Dn Slope=0.005
Boundary for River Rch & Prof#=Elm 31,Reach-1,3
Up Type=0
Dn Type=3
Dn Slope=0.005
Boundary for River Rch & Prof#=Elm 31,Reach-1,4
Up Type=0
Dn Type=3
Dn Slope=0.005
Boundary for River Rch & Prof#=Elm 31,Reach-1,5
Up Type=0
Dn Type=3
Dn Slope=0.005
Boundary for River Rch & Prof#=Elm 31,Reach-1,6
Up Type=0
Dn Type=3
Dn Slope=0.005
Boundary for River Rch & Prof#=Elm 31,Reach-1,7
Up Type=0
Dn Type=3
Dn Slope=0.005

--- Elm 31.g01 (geometry) ---

Geom Title=Existing Conditions

River Reach=Elm 31,Reach-1
Reach XY= 30
      1493155.00      6767238.00      1493453.54      6767184.46
      1493611.04      6767039.62      1493753.57      6767084.93
      1493820.90      6766988.54      1494294.50      6767036.78
      1495265.69      6766738.76      1495555.00      6766838.00
      1495935.23      6766558.13      1496012.86      6766331.83
      1496198.94      6766145.48      1496794.50      6766286.80
      1497356.55      6765991.75      1497539.17      6765988.66
      1497702.76      6766243.93      1497706.20      6766527.50
      1497818.26      6766801.66      1498451.55      6767089.48
      1498310.02      6768032.77      1498515.42      6768186.98
      1498894.50      6768186.78      1499103.64      6768126.46
      1499012.84      6767840.93      1499799.29      6767790.59
      1499808.06      6767196.28      1500294.93      6767048.00
      1500262.75      6766934.36      1500445.57      6766694.61
      1500406.86      6766594.13      1500555.00      6766238.00

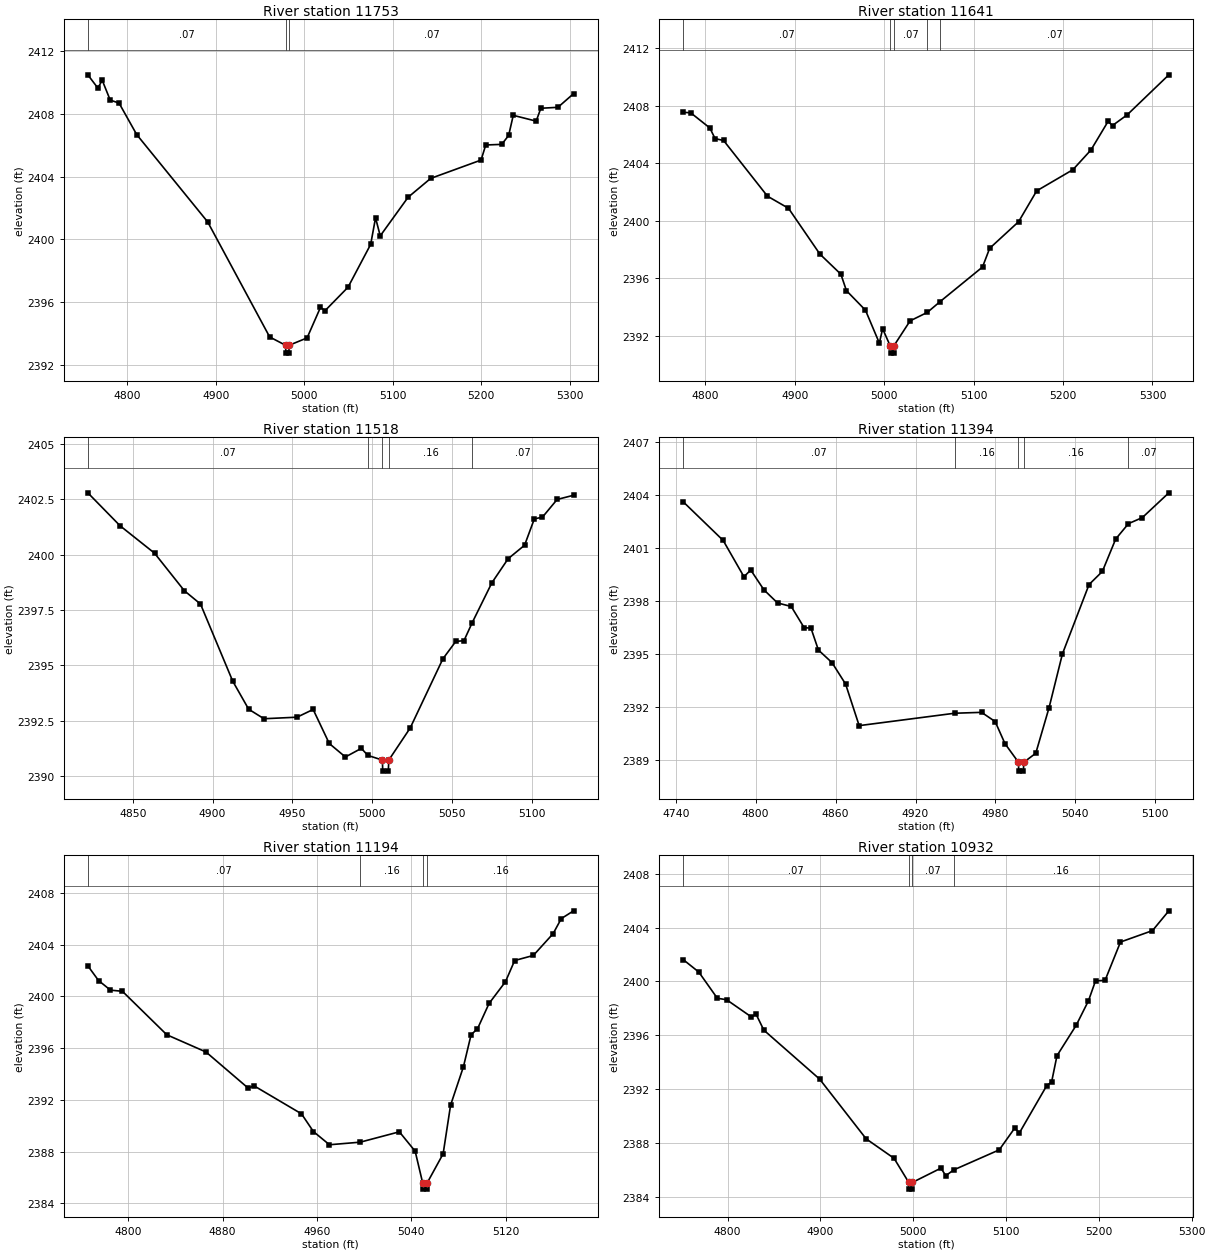
Type RM Length L Ch R = 1,11753,112,112,112
BEGIN DESCRIPTION:
elmc656
END DESCRIPTION:
XS GIS Cut Line= 3
      1493340.72      6767433.24      1493326.44      6767188.86
      1493226.77      6766901.24
#Sta/Elev= 30
  4755.2 2410.48  4766.5 2409.64  4771.5 2410.13  4780.5 2408.87  4790.5 2408.68
  4810.5 2406.67  4890.7 2401.11  4960.8 2393.78  4978.8 2393.25  4979.1 2392.75
  4982.6 2392.75  4982.8 2393.25  5003.1 2393.72  5018.2 2395.66  5023.5 2395.46
  5049.4 2396.95  5075.0 2399.68  5080.5 2401.37  5085.8 2400.22  5117.3 2402.68
  5142.8 2403.88  5199.8 2405.05  5205.1 2406.01  5223.2 2406.05  5231.0 2406.62
  5236.2 2407.90  5262.1 2407.53  5267.4 2408.35  5286.7 2408.41  5304.4 2409.28
#Mann=3,-1,0
  4755.2    0.07       0  4978.8    0.07       0  4982.8    0.07       0
Bank Sta=4978.8,4982.8
Exp/Cntr=0.3,0.1

Type RM Length L Ch R = 1,11641,123,123,123
BEGIN DESCRIPTION:
elmc657
END DESCRIPTION:
XS GIS Cut Line= 3
      1493555.55      6767378.55      1493438.12      6767186.62
      1493390.38      6766871.92
#Sta/Elev= 30
  4775.0 2407.54  4783.6 2407.50  4804.9 2406.45  4810.8 2405.71  4820.3 2405.58
  4869.4 2401.71  4892.9 2400.87  4928.0 2397.69  4951.5 2396.29  4957.7 2395.15
  4979.0 2393.79  4994.5 2391.51  4998.2 2392.50  5006.7 2391.31  5007.0 2390.81
  5010.5 2390.81  5010.7 2391.31  5028.9 2393.05  5048.2 2393.64  5062.3 2394.38
  5109.9 2396.79  5117.9 2398.09  5150.3 2399.94  5170.5 2402.08  5211.0 2403.55
  5231.2 2404.92  5250.3 2406.90  5255.3 2406.62  5271.7 2407.36  5318.3 2410.14
#Mann=5,-1,0
  4775.0    0.07       0  5006.7    0.07       0  5010.7    0.07       0
  5048.2    0.16       0  5062.3    0.07       0
Bank Sta=5006.7,5010.7
Exp/Cntr=0.3,0.1

Type RM Length L Ch R = 1,11518,124,124,124
BEGIN DESCRIPTION:
elmc362
END DESCRIPTION:
XS GIS Cut Line= 3
      1493555.00      6767287.98      1493531.74      6767111.31
      1493504.99      6766987.97
#Sta/Elev= 30
  4821.8 2402.80  4842.0 2401.31  4863.6 2400.07  4882.3 2398.37  4892.4 2397.77
  4912.6 2394.28  4922.6 2393.01  4932.2 2392.58  4952.9 2392.65  4963.0 2393.00
  4973.1 2391.46  4983.2 2390.85  4993.2 2391.24  4997.3 2390.92  5006.4 2390.71
  5006.6 2390.21  5010.1 2390.21  5010.4 2390.71  5023.8 2392.16  5044.3 2395.29
  5052.4 2396.08  5057.5 2396.11  5062.7 2396.93  5075.0 2398.73  5085.2 2399.82
  5095.5 2400.43  5101.6 2401.62  5106.7 2401.70  5115.9 2402.50  5126.2 2402.69
#Mann=5,-1,0
  4821.8    0.07       0  4997.3    0.16       0  5006.4    0.07       0
  5010.4    0.16       0  5062.7    0.07       0
Bank Sta=5006.4,5010.4
Exp/Cntr=0.3,0.1

Type RM Length L Ch R = 1,11394,200,200,200
BEGIN DESCRIPTION:
elmc655
END DESCRIPTION:
XS GIS Cut Line= 3
      1493679.28      6767287.48      1493627.18      6767034.84
      1493628.49      6766928.11
#Sta/Elev= 30
  4745.5 2403.61  4775.6 2401.42  4791.2 2399.37  4796.3 2399.75  4806.2 2398.63
  4816.4 2397.89  4826.7 2397.69  4836.4 2396.49  4841.5 2396.47  4847.1 2395.23
  4857.3 2394.52  4867.5 2393.31  4877.7 2390.96  4949.4 2391.66  4969.6 2391.71
  4979.8 2391.19  4987.2 2389.94  4997.3 2388.89  4997.5 2388.39  5001.0 2388.39
  5001.3 2388.89  5010.3 2389.40  5020.3 2391.98  5030.3 2395.01  5050.3 2398.93
  5060.3 2399.67  5070.3 2401.50  5079.9 2402.37  5090.3 2402.71  5110.2 2404.11
#Mann=5,-1,0
  4745.5    0.07       0  4949.4    0.16       0  4997.3    0.07       0
  5001.3    0.16       0  5079.9    0.07       0
Bank Sta=4997.3,5001.3
Exp/Cntr=0.3,0.1

Type RM Length L Ch R = 1,11194,262,262,262
BEGIN DESCRIPTION:
elmc654
END DESCRIPTION:
XS GIS Cut Line= 3
      1493830.30      6767276.99      1493795.15      6767043.95
      1493726.52      6766882.07
#Sta/Elev= 30
  4765.9 2402.36  4775.0 2401.22  4785.1 2400.48  4795.2 2400.39  4832.8 2397.03
  4866.0 2395.70  4901.7 2392.91  4906.8 2393.08  4946.9 2390.92  4957.0 2389.55
  4970.6 2388.53  4996.7 2388.73  5029.8 2389.53  5043.2 2388.03  5049.5 2385.60
  5049.7 2385.10  5053.2 2385.10  5053.5 2385.60  5066.9 2387.83  5073.2 2391.59
  5084.1 2394.56  5090.6 2397.04  5096.0 2397.49  5105.8 2399.45  5119.7 2401.13
  5127.5 2402.77  5143.3 2403.16  5160.1 2404.85  5167.0 2406.01  5177.4 2406.61
#Mann=4,-1,0
  4765.9    0.07       0  4996.7    0.16       0  5049.5    0.07       0
  5053.5    0.16       0
Bank Sta=5049.5,5053.5
Exp/Cntr=0.3,0.1

Type RM Length L Ch R = 1,10932,230,230,230
BEGIN DESCRIPTION:
elmc653
END DESCRIPTION:
XS GIS Cut Line= 3
      1493985.26      6767284.82      1494000.88      6767037.44
      1494073.46      6766771.74
#Sta/Elev= 30
  4752.1 2401.63  4769.0 2400.70  4789.0 2398.75  4799.0 2398.64  4825.7 2397.36
  4830.7 2397.57  4839.1 2396.38  4899.2 2392.74  4949.3 2388.30  4979.4 2386.85
  4995.2 2385.06  4995.4 2384.56  4998.9 2384.56  4999.2 2385.06  5029.9 2386.12
  5035.1 2385.56  5043.7 2385.99  5092.7 2387.48  5109.3 2389.09  5114.5 2388.75
  5143.9 2392.26  5149.1 2392.52  5154.9 2394.48  5175.6 2396.74  5188.8 2398.56
  5196.4 2400.04  5206.7 2400.08  5223.3 2402.93  5257.8 2403.78  5275.4 2405.25
#Mann=4,-1,0
  4752.1    0.07       0  4995.2    0.07       0  4999.2    0.07       0
  5043.7    0.16       0
Bank Sta=4995.2,4999.2
Exp/Cntr=0.3,0.1

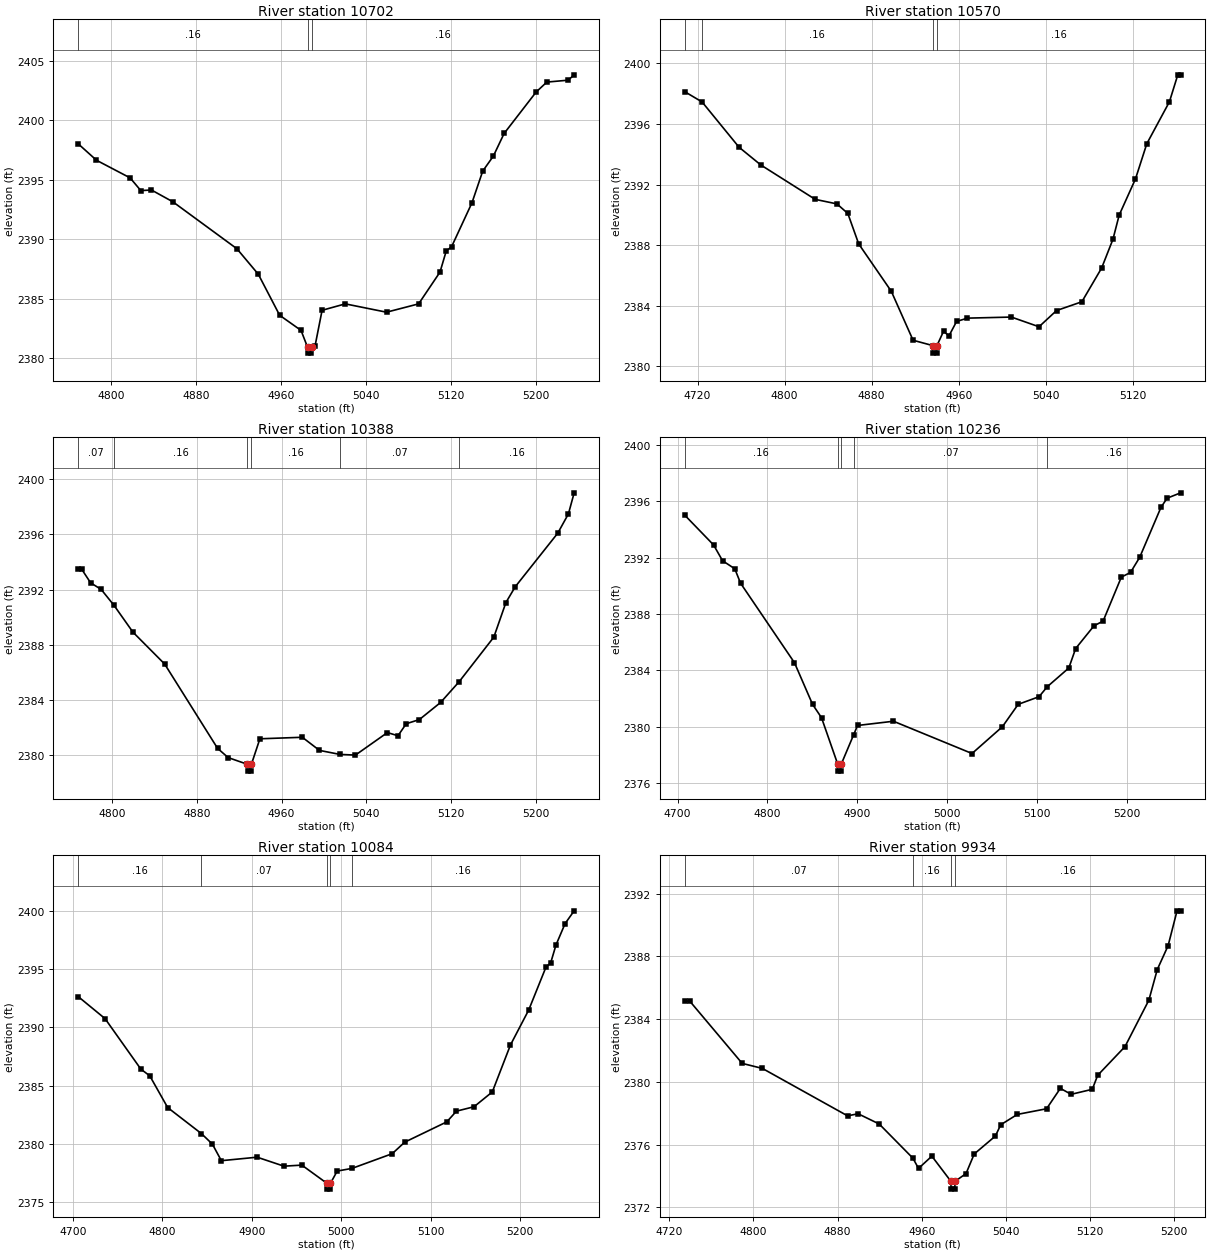
Type RM Length L Ch R = 1,10702,132,132,132
BEGIN DESCRIPTION:
elmc652
END DESCRIPTION:
XS GIS Cut Line= 3
      1494207.92      6767266.56      1494231.35      6767033.54
      1494207.98      6766802.41
#Sta/Elev= 30
  4769.2 2398.03  4786.4 2396.65  4818.0 2395.17  4828.1 2394.10  4838.1 2394.15
  4858.2 2393.16  4918.5 2389.21  4938.6 2387.07  4958.7 2383.62  4978.8 2382.35
  4984.9 2380.94  4985.1 2380.44  4988.6 2380.44  4988.9 2380.94  4991.9 2381.01
  4998.6 2384.04  5020.4 2384.58  5059.2 2383.88  5089.4 2384.58  5109.5 2387.25
  5115.4 2389.03  5120.4 2389.38  5139.6 2393.08  5149.7 2395.74  5159.7 2397.00
  5169.8 2398.90  5199.9 2402.38  5210.0 2403.22  5230.1 2403.38  5235.7 2403.83
#Mann=3,-1,0
  4769.2    0.16       0  4984.9    0.07       0  4988.9    0.16       0
Bank Sta=4984.9,4988.9
Exp/Cntr=0.3,0.1

Type RM Length L Ch R = 1,10570,182,182,182
BEGIN DESCRIPTION:
elmc361
END DESCRIPTION:
XS GIS Cut Line= 3
      1494355.00      6767287.98      1494348.94      6766996.14
      1494305.01      6766838.03
#Sta/Elev= 30
  4708.1 2398.14  4724.1 2397.46  4758.1 2394.47  4778.1 2393.30  4828.1 2391.03
  4848.1 2390.73  4858.1 2390.10  4868.1 2388.09  4898.1 2384.96  4918.1 2381.73
  4936.1 2381.38  4936.4 2380.88  4939.9 2380.88  4940.1 2381.38  4946.1 2382.32
  4951.1 2382.02  4958.1 2382.97  4968.1 2383.19  5008.5 2383.26  5033.9 2382.62
  5050.0 2383.69  5073.3 2384.27  5091.5 2386.50  5101.9 2388.40  5107.6 2389.99
  5122.6 2392.38  5133.0 2394.70  5153.8 2397.47  5161.5 2399.25  5164.1 2399.25
#Mann=4,-1,0
  4708.1    0.07       0  4724.1    0.16       0  4936.1    0.07       0
  4940.1    0.16       0
Bank Sta=4936.1,4940.1
Exp/Cntr=0.3,0.1

Type RM Length L Ch R = 1,10388,152,152,152
BEGIN DESCRIPTION:
elmc651
END DESCRIPTION:
XS GIS Cut Line= 3
      1494524.32      6767219.70      1494529.53      6766990.57
      1494502.22      6766752.62
#Sta/Elev= 30
  4767.8 2393.47  4771.1 2393.47  4779.5 2392.49  4789.5 2392.01  4801.6 2390.86
  4819.5 2388.92  4849.5 2386.61  4899.5 2380.51  4909.5 2379.84  4927.5 2379.36
  4927.8 2378.86  4931.3 2378.86  4931.5 2379.36  4939.5 2381.20  4979.6 2381.31
  4995.8 2380.36  5015.1 2380.07  5029.8 2380.02  5060.0 2381.65  5070.0 2381.42
  5077.8 2382.29  5090.2 2382.59  5110.3 2383.83  5127.8 2385.33  5160.6 2388.56
  5172.0 2391.06  5180.8 2392.20  5221.0 2396.08  5231.1 2397.48  5236.5 2399.00
#Mann=6,-1,0
  4767.8    0.07       0  4801.6    0.16       0  4927.5    0.07       0
  4931.5    0.16       0  5015.1    0.07       0  5127.8    0.16       0
Bank Sta=4927.5,4931.5
Exp/Cntr=0.3,0.1

Type RM Length L Ch R = 1,10236,152,152,152
BEGIN DESCRIPTION:
elmc650
END DESCRIPTION:
XS GIS Cut Line= 3
      1494683.17      6767230.13      1494666.25      6766941.09
      1494615.47      6766683.28
#Sta/Elev= 30
  4707.8 2395.02  4740.0 2392.90  4750.0 2391.78  4763.6 2391.21  4770.0 2390.19
  4830.1 2384.54  4850.2 2381.59  4860.2 2380.64  4878.2 2377.35  4878.5 2376.85
  4882.0 2376.85  4882.2 2377.35  4895.9 2379.42  4900.3 2380.09  4940.3 2380.39
  5027.8 2378.10  5061.6 2380.00  5079.2 2381.59  5102.4 2382.13  5111.6 2382.84
  5135.6 2384.17  5143.2 2385.55  5163.6 2387.16  5173.8 2387.50  5194.1 2390.62
  5204.3 2390.95  5214.5 2392.02  5238.3 2395.58  5245.1 2396.22  5260.1 2396.60
#Mann=5,-1,0
  4707.8    0.16       0  4878.2    0.07       0  4882.2    0.16       0
  4895.9    0.07       0  5111.6    0.16       0
Bank Sta=4878.2,4882.2
Exp/Cntr=0.3,0.1

Type RM Length L Ch R = 1,10084,150,150,150
BEGIN DESCRIPTION:
elmc360
END DESCRIPTION:
XS GIS Cut Line= 3
      1494805.00      6767188.01      1494802.82      6766894.12
      1494755.01      6766638.04
#Sta/Elev= 30
  4706.1 2392.64  4736.1 2390.75  4776.1 2386.42  4786.1 2385.84  4806.1 2383.12
  4843.9 2380.88  4856.1 2379.98  4866.1 2378.56  4906.1 2378.86  4936.1 2378.09
  4956.1 2378.18  4984.1 2376.62  4984.4 2376.12  4987.9 2376.12  4988.1 2376.62
  4995.6 2377.67  5012.2 2377.90  5057.1 2379.16  5071.1 2380.15  5118.1 2381.89
  5128.9 2382.81  5148.6 2383.19  5169.0 2384.46  5189.3 2388.49  5209.7 2391.49
  5229.1 2395.19  5234.2 2395.52  5240.2 2397.07  5250.4 2398.91  5260.5 2400.00
#Mann=5,-1,0
  4706.1    0.16       0  4843.9    0.07       0  4984.1    0.07       0
  4988.1    0.07       0  5012.2    0.16       0
Bank Sta=4984.1,4988.1
Exp/Cntr=0.3,0.1

Type RM Length L Ch R = 1,9934,184,184,184
BEGIN DESCRIPTION:
elmc649
END DESCRIPTION:
XS GIS Cut Line= 3
      1494955.31      6767102.59      1494937.08      6766835.62
      1494892.80      6766636.37
#Sta/Elev= 30
  4734.6 2385.15  4739.4 2385.15  4789.3 2381.18  4808.5 2380.86  4889.5 2377.84
  4899.6 2377.97  4919.6 2377.32  4951.7 2375.14  4957.0 2374.49  4969.7 2375.27
  4987.8 2373.67  4988.0 2373.17  4991.5 2373.17  4991.8 2373.67  5002.2 2374.16
  5010.0 2375.41  5030.1 2376.55  5035.2 2377.27  5051.0 2377.93  5078.8 2378.29
  5091.9 2379.59  5102.2 2379.21  5122.3 2379.53  5127.4 2380.42  5153.4 2382.25
  5176.1 2385.21  5184.1 2387.16  5194.4 2388.68  5202.9 2390.90  5206.3 2390.90
#Mann=4,-1,0
  4734.6    0.07       0  4951.7    0.16       0  4987.8    0.07       0
  4991.8    0.16       0
Bank Sta=4987.8,4991.8
Exp/Cntr=0.3,0.1

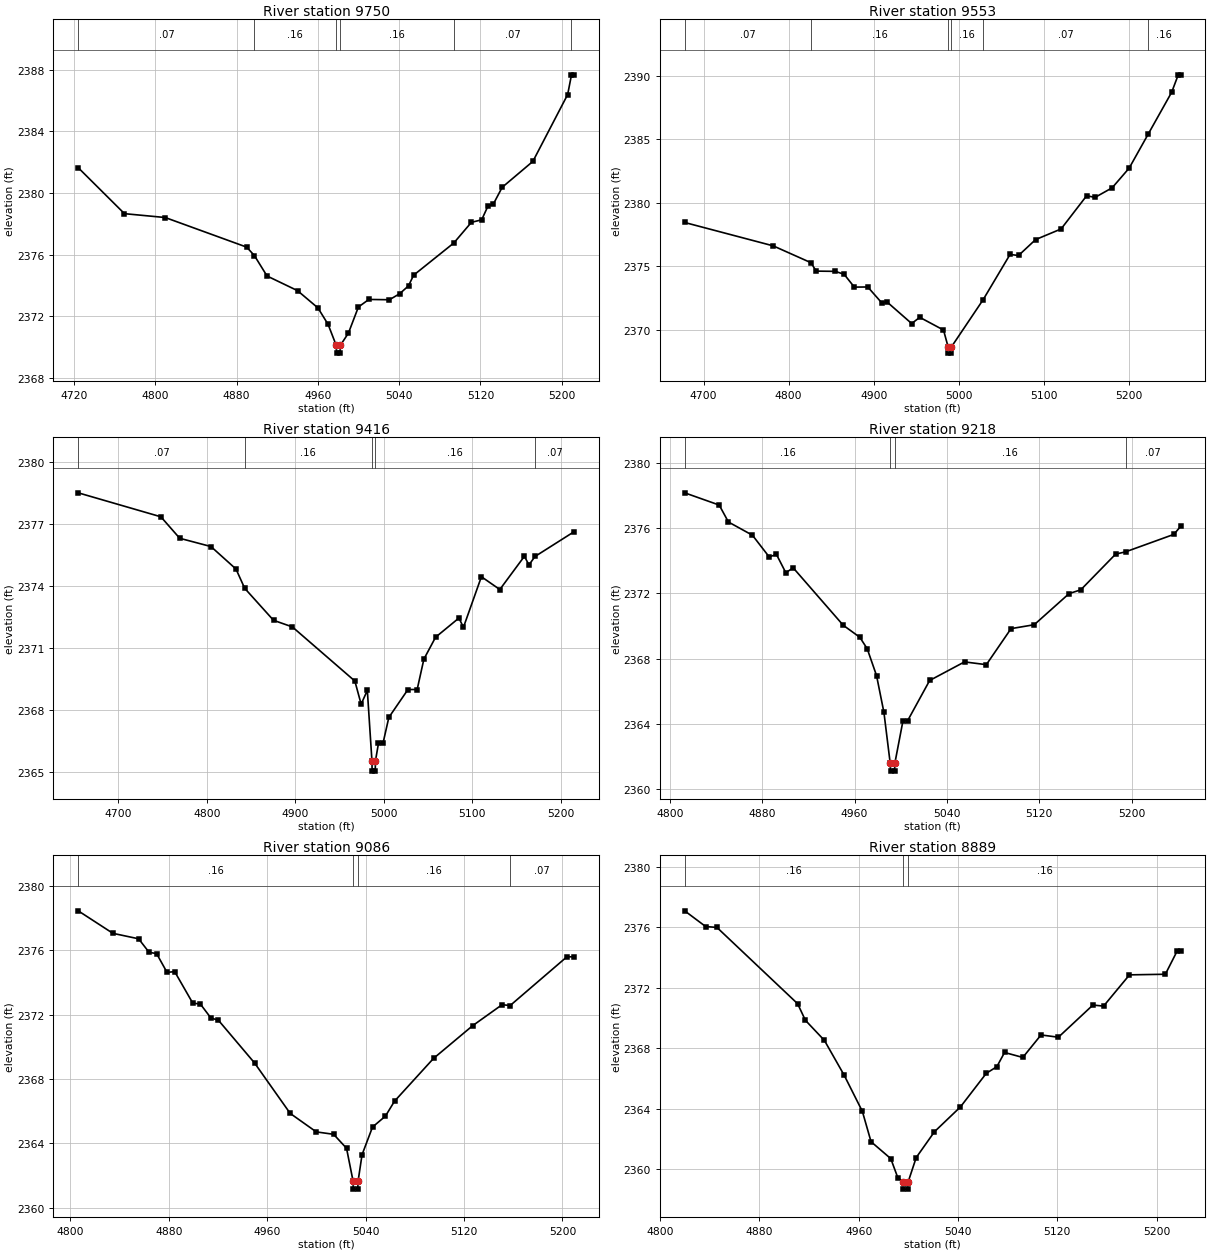
Type RM Length L Ch R = 1,9750,197,197,197
BEGIN DESCRIPTION:
elmc648
END DESCRIPTION:
XS GIS Cut Line= 3
      1495089.43      6767063.46      1495106.35      6766783.54
      1495079.00      6766577.78
#Sta/Elev= 30
  4724.2 2381.64  4769.7 2378.66  4809.8 2378.41  4890.0 2376.49  4897.6 2375.94
  4910.0 2374.62  4940.0 2373.67  4960.1 2372.55  4970.1 2371.48  4978.1 2370.12
  4978.4 2369.62  4981.9 2369.62  4982.1 2370.12  4990.1 2370.92  4999.9 2372.61
  5010.2 2373.10  5030.4 2373.08  5040.5 2373.47  5049.2 2373.98  5054.2 2374.67
  5093.8 2376.76  5111.1 2378.10  5121.2 2378.26  5127.5 2379.17  5132.5 2379.26
  5141.4 2380.37  5171.6 2382.05  5205.8 2386.38  5209.5 2387.63  5212.2 2387.66
#Mann=6,-1,0
  4724.2    0.07       0  4897.6    0.16       0  4978.1    0.07       0
  4982.1    0.16       0  5093.8    0.07       0  5209.5    0.16       0
Bank Sta=4978.1,4982.1
Exp/Cntr=0.3,0.1

Type RM Length L Ch R = 1,9553,137,137,137
BEGIN DESCRIPTION:
elmc647
END DESCRIPTION:
XS GIS Cut Line= 3
      1495142.81      6767025.72      1495287.34      6766741.87
      1495286.04      6766477.50
#Sta/Elev= 30
  4677.8 2378.43  4781.8 2376.59  4826.3 2375.26  4832.3 2374.60  4854.8 2374.58
  4865.2 2374.35  4877.2 2373.34  4893.0 2373.35  4909.7 2372.08  4915.3 2372.19
  4944.6 2370.47  4954.1 2370.96  4982.0 2369.96  4987.4 2368.64  4987.7 2368.14
  4991.2 2368.14  4991.4 2368.64  5028.7 2372.36  5060.2 2375.91  5070.2 2375.83
  5090.2 2377.08  5120.2 2377.92  5150.2 2380.53  5160.2 2380.41  5180.2 2381.16
  5200.2 2382.71  5222.5 2385.38  5250.2 2388.69  5257.9 2390.06  5260.7 2390.06
#Mann=6,-1,0
  4677.8    0.07       0  4826.3    0.16       0  4987.4    0.07       0
  4991.4    0.16       0  5028.7    0.07       0  5222.5    0.16       0
Bank Sta=4987.4,4991.4
Exp/Cntr=0.3,0.1

Type RM Length L Ch R = 1,9416,198,198,198
BEGIN DESCRIPTION:
elmc646
END DESCRIPTION:
XS GIS Cut Line= 3
      1495164.93      6767040.06      1495407.13      6766795.25
      1495464.41      6766586.96
#Sta/Elev= 30
  4654.6 2378.49  4748.0 2377.33  4769.3 2376.29  4804.6 2375.89  4832.9 2374.80
  4842.7 2373.87  4875.3 2372.32  4896.6 2372.00  4967.2 2369.38  4974.3 2368.26
  4981.3 2368.93  4986.5 2365.52  4986.7 2365.02  4990.2 2365.02  4990.5 2365.52
  4993.9 2366.37  4999.0 2366.37  5005.6 2367.62  5027.2 2368.97  5037.6 2368.97
  5045.2 2370.44  5058.4 2371.50  5084.8 2372.43  5089.9 2371.98  5110.2 2374.43
  5131.0 2373.81  5158.8 2375.42  5163.9 2375.00  5170.8 2375.41  5215.0 2376.61
#Mann=5,-1,0
  4654.6    0.07       0  4842.7    0.16       0  4986.5    0.07       0
  4990.5    0.16       0  5170.8    0.07       0
Bank Sta=4986.5,4990.5
Exp/Cntr=0.3,0.1

Type RM Length L Ch R = 1,9218,132,132,132
BEGIN DESCRIPTION:
elmc645
END DESCRIPTION:
XS GIS Cut Line= 3
      1495696.21      6766959.34      1495579.01      6766810.88
      1495550.46      6766572.13
#Sta/Elev= 30
  4812.8 2378.17  4842.7 2377.42  4850.7 2376.38  4871.5 2375.57  4886.0 2374.24
  4892.3 2374.39  4900.4 2373.27  4906.8 2373.57  4950.1 2370.05  4964.5 2369.31
  4970.9 2368.61  4979.0 2366.96  4985.4 2364.70  4990.8 2361.60  4991.1 2361.10
  4994.6 2361.10  4994.9 2361.60  5001.9 2364.19  5005.9 2364.19  5025.0 2366.66
  5055.2 2367.80  5074.1 2367.63  5095.5 2369.84  5115.6 2370.08  5145.8 2371.99
  5155.9 2372.22  5186.1 2374.41  5194.7 2374.55  5236.5 2375.62  5242.4 2376.11
#Mann=4,-1,0
  4812.8    0.16       0  4990.8    0.07       0  4994.9    0.16       0
  5194.7    0.07       0
Bank Sta=4990.8,4994.9
Exp/Cntr=0.3,0.1

Type RM Length L Ch R = 1,9086,197,197,197
BEGIN DESCRIPTION:
elmc644
END DESCRIPTION:
XS GIS Cut Line= 3
      1495805.57      6766907.24      1495689.68      6766748.38
      1495624.78      6766552.38
#Sta/Elev= 30
  4806.4 2378.46  4834.6 2377.06  4855.5 2376.72  4864.0 2375.88  4870.1 2375.80
  4878.6 2374.63  4884.8 2374.68  4899.5 2372.72  4905.7 2372.66  4914.2 2371.80
  4920.4 2371.65  4949.7 2369.00  4978.7 2365.86  4999.9 2364.71  5014.0 2364.56
  5024.5 2363.69  5029.8 2361.65  5030.0 2361.15  5033.6 2361.15  5033.9 2361.65
  5037.1 2363.29  5045.6 2365.01  5056.1 2365.69  5063.5 2366.62  5095.2 2369.28
  5126.9 2371.31  5150.9 2372.62  5157.5 2372.57  5203.6 2375.60  5209.5 2375.60
#Mann=4,-1,0
  4806.4    0.16       0  5029.8    0.07       0  5033.9    0.16       0
  5157.5    0.07       0
Bank Sta=5029.8,5033.9
Exp/Cntr=0.3,0.1

Type RM Length L Ch R = 1,8889,199,199,199
BEGIN DESCRIPTION:
elmc643
END DESCRIPTION:
XS GIS Cut Line= 3
      1495934.49      6766792.68      1495849.84      6766642.91
      1495717.02      6766458.00
#Sta/Elev= 30
  4819.7 2377.10  4836.6 2376.06  4845.7 2376.00  4910.7 2370.95  4917.0 2369.85
  4932.3 2368.52  4948.2 2366.22  4962.9 2363.82  4969.9 2361.81  4985.8 2360.69
  4991.5 2359.42  4995.8 2359.17  4996.0 2358.67  4999.6 2358.67  4999.9 2359.17
  5006.3 2360.76  5021.0 2362.47  5041.9 2364.11  5062.8 2366.34  5071.3 2366.78
  5077.5 2367.72  5092.2 2367.39  5106.9 2368.88  5120.9 2368.73  5148.7 2370.86
  5157.3 2370.79  5178.2 2372.86  5207.1 2372.90  5216.8 2374.47  5219.4 2374.47
#Mann=3,-1,0
  4819.7    0.16       0  4995.8    0.07       0  4999.9    0.16       0
Bank Sta=4995.8,4999.9
Exp/Cntr=0.3,0.1

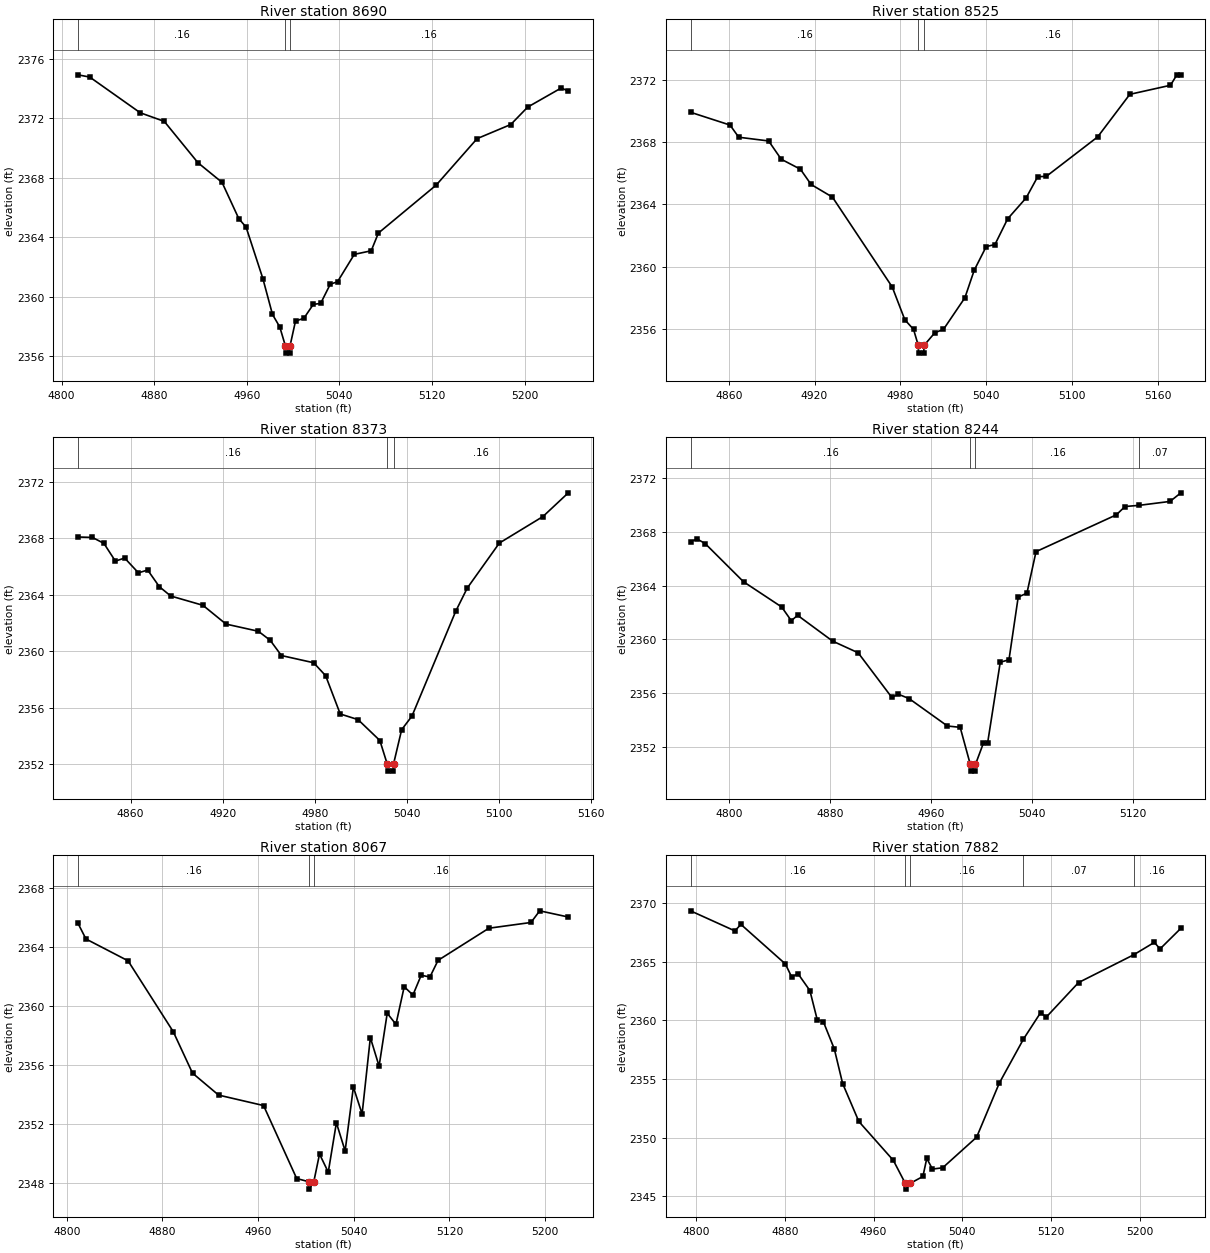
Type RM Length L Ch R = 1,8690,165,165,165
BEGIN DESCRIPTION:
elmc642
END DESCRIPTION:
XS GIS Cut Line= 3
      1496108.92      6766598.62      1495959.22      6766484.06
      1495771.84      6766341.91
#Sta/Elev= 30
  4814.1 2374.91  4824.3 2374.76  4867.9 2372.36  4888.7 2371.78  4917.8 2369.00
  4938.6 2367.68  4953.1 2365.24  4959.4 2364.67  4973.9 2361.21  4982.2 2358.80
  4988.5 2357.96  4993.3 2356.70  4993.5 2356.20  4997.1 2356.20  4997.4 2356.70
  5002.1 2358.36  5009.3 2358.54  5017.5 2359.48  5023.8 2359.54  5032.1 2360.83
  5038.4 2361.00  5052.9 2362.84  5067.5 2363.08  5073.7 2364.27  5123.7 2367.50
  5159.0 2370.62  5188.1 2371.57  5202.7 2372.74  5231.8 2374.03  5237.8 2373.81
#Mann=3,-1,0
  4814.1    0.16       0  4993.3    0.07       0  4997.4    0.16       0
Bank Sta=4993.3,4997.4
Exp/Cntr=0.3,0.1

Type RM Length L Ch R = 1,8525,152,152,152
BEGIN DESCRIPTION:
elmc641
END DESCRIPTION:
XS GIS Cut Line= 3
      1496148.02      6766431.98      1496011.30      6766336.92
      1495865.43      6766237.94
#Sta/Elev= 30
  4833.3 2369.91  4860.9 2369.09  4867.0 2368.31  4887.9 2368.07  4896.7 2366.90
  4910.1 2366.26  4917.6 2365.28  4932.5 2364.47  4974.3 2358.71  4983.1 2356.61
  4989.2 2355.99  4992.5 2354.97  4992.7 2354.47  4996.3 2354.47  4996.6 2354.97
  5004.1 2355.78  5010.1 2355.99  5025.1 2358.02  5031.6 2359.78  5040.0 2361.30
  5046.1 2361.43  5055.0 2363.08  5067.9 2364.42  5076.0 2365.78  5082.0 2365.80
  5117.9 2368.33  5140.4 2371.06  5168.8 2371.64  5173.3 2372.31  5176.1 2372.31
#Mann=3,-1,0
  4833.3    0.16       0  4992.5    0.07       0  4996.6    0.16       0
Bank Sta=4992.5,4996.6
Exp/Cntr=0.3,0.1

Type RM Length L Ch R = 1,8373,129,129,129
BEGIN DESCRIPTION:
elmc640
END DESCRIPTION:
XS GIS Cut Line= 3
      1496214.40      6766372.04      1496119.37      6766230.15
      1496008.72      6766131.08
#Sta/Elev= 30
  4825.7 2368.09  4835.1 2368.06  4842.6 2367.64  4850.1 2366.38  4856.1 2366.60
  4865.1 2365.55  4871.1 2365.75  4878.7 2364.57  4886.1 2363.91  4907.1 2363.25
  4922.1 2361.92  4943.2 2361.41  4950.9 2360.77  4958.2 2359.69  4979.2 2359.18
  4987.0 2358.26  4996.5 2355.55  5008.1 2355.15  5022.3 2353.67  5027.1 2352.00
  5027.4 2351.50  5031.0 2351.50  5031.2 2352.00  5036.5 2354.44  5043.2 2355.40
  5071.7 2362.83  5079.2 2364.47  5100.1 2367.66  5128.5 2369.54  5145.0 2371.22
#Mann=3,-1,0
  4825.7    0.16       0  5027.1    0.07       0  5031.2    0.16       0
Bank Sta=5027.1,5031.2
Exp/Cntr=0.3,0.1

Type RM Length L Ch R = 1,8244,177,177,177
BEGIN DESCRIPTION:
elmc639
END DESCRIPTION:
XS GIS Cut Line= 3
      1496240.47      6766369.51      1496210.52      6766136.40
      1496105.06      6766025.73
#Sta/Elev= 30
  4769.8 2367.27  4774.9 2367.49  4781.4 2367.14  4811.7 2364.30  4841.9 2362.42
  4849.5 2361.40  4854.5 2361.80  4882.2 2359.88  4902.4 2359.01  4929.0 2355.69
  4934.1 2355.93  4942.7 2355.60  4973.0 2353.56  4983.1 2353.46  4991.1 2350.70
  4991.3 2350.20  4994.9 2350.20  4995.2 2350.70  5001.5 2352.29  5004.8 2352.29
  5014.8 2358.31  5021.7 2358.49  5029.0 2363.16  5035.9 2363.45  5043.1 2366.54
  5106.6 2369.28  5113.5 2369.90  5124.8 2369.99  5149.1 2370.28  5157.7 2370.92
#Mann=4,-1,0
  4769.8    0.16       0  4991.1    0.07       0  4995.2    0.16       0
  5124.8    0.07       0
Bank Sta=4991.1,4995.2
Exp/Cntr=0.3,0.1

Type RM Length L Ch R = 1,8067,185,185,185
BEGIN DESCRIPTION:
elmc638
END DESCRIPTION:
XS GIS Cut Line= 3
      1496282.11      6766353.88      1496373.28      6766188.48
      1496211.78      6766037.41
#Sta/Elev= 30
  4809.4 2365.62  4816.1 2364.55  4851.3 2363.07  4889.1 2358.26  4905.2 2355.45
  4927.0 2353.96  4964.6 2353.25  4992.3 2348.30  5002.5 2348.08  5002.7 2347.58
  5006.6 2348.08  5011.4 2349.96  5018.7 2348.73  5025.5 2352.08  5032.8 2350.17
  5039.7 2354.50  5047.0 2352.68  5053.9 2357.86  5061.2 2355.92  5068.0 2359.51
  5075.3 2358.76  5082.2 2361.31  5089.5 2360.75  5096.4 2362.09  5103.7 2361.97
  5110.5 2363.10  5153.0 2365.28  5188.2 2365.67  5195.5 2366.46  5219.4 2366.04
#Mann=3,-1,0
  4809.4    0.16       0  5002.5    0.07       0  5006.6    0.16       0
Bank Sta=5002.5,5006.6
Exp/Cntr=0.3,0.1

Type RM Length L Ch R = 1,7882,194,194,194
BEGIN DESCRIPTION:
elmc637
END DESCRIPTION:
XS GIS Cut Line= 3
      1496451.41      6766425.44      1496538.64      6766237.96
      1496584.21      6766007.51
#Sta/Elev= 30
  4795.1 2369.35  4835.0 2367.64  4840.5 2368.19  4880.5 2364.82  4886.3 2363.69
  4891.8 2364.00  4902.6 2362.55  4909.2 2360.07  4914.7 2359.90  4924.6 2357.57
  4932.1 2354.62  4946.7 2351.38  4977.8 2348.06  4988.5 2346.11  4988.9 2345.61
  4993.1 2346.11  5004.4 2346.69  5007.9 2348.23  5013.0 2347.32  5022.2 2347.43
  5052.8 2350.04  5073.2 2354.65  5095.0 2358.41  5110.4 2360.66  5115.5 2360.28
  5144.6 2363.23  5194.3 2365.60  5212.9 2366.66  5218.0 2366.10  5236.8 2367.86
#Mann=5,-1,0
  4795.1    0.16       0  4988.5    0.07       0  4993.1    0.16       0
  5095.0    0.07       0  5194.3    0.16       0
Bank Sta=4988.5,4993.1
Exp/Cntr=0.3,0.1

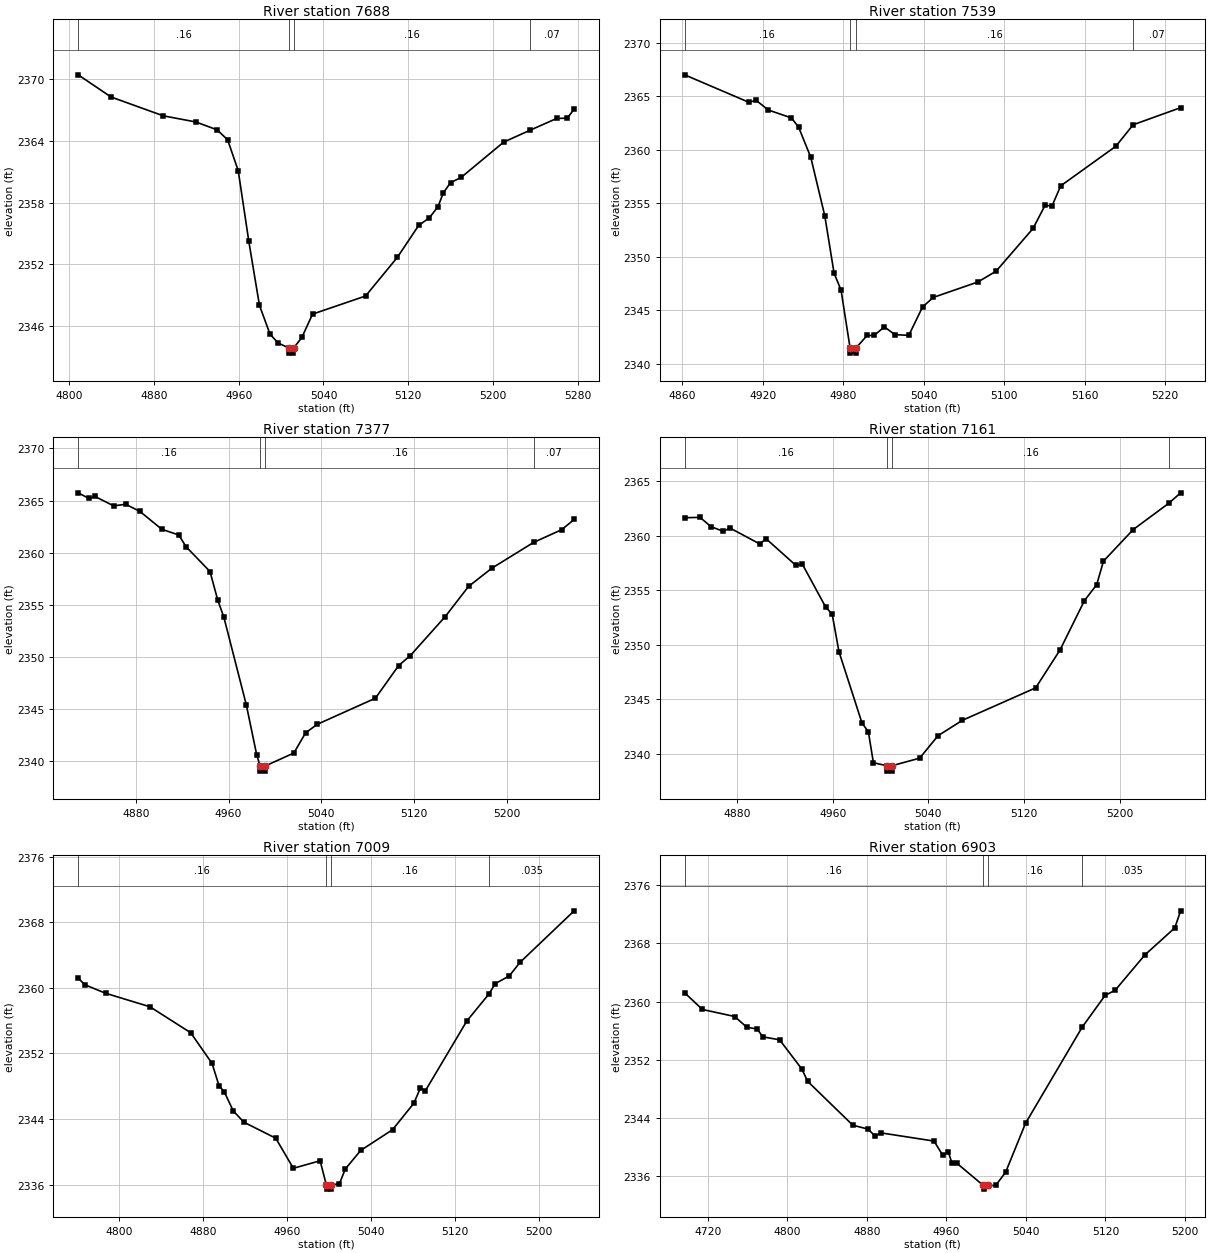
Type RM Length L Ch R = 1,7688,149,149,149
BEGIN DESCRIPTION:
elmc359
END DESCRIPTION:
XS GIS Cut Line= 3
      1496722.24      6766478.85      1496717.16      6766287.62
      1496704.08      6766011.53
#Sta/Elev= 30
  4808.7 2370.41  4839.6 2368.26  4888.8 2366.43  4919.6 2365.83  4939.6 2365.07
  4949.6 2364.10  4959.6 2361.10  4969.6 2354.22  4979.6 2348.02  4989.6 2345.21
  4997.3 2344.35  5007.3 2343.87  5007.6 2343.37  5011.6 2343.37  5011.9 2343.87
  5019.6 2344.89  5029.7 2347.16  5079.7 2348.92  5109.7 2352.68  5129.8 2355.78
  5139.8 2356.51  5148.0 2357.60  5153.0 2358.94  5159.8 2359.93  5169.8 2360.44
  5209.9 2363.87  5235.1 2365.04  5259.9 2366.17  5269.9 2366.20  5276.4 2367.07
#Mann=4,-1,0
  4808.7    0.16       0  5007.3    0.07       0  5011.9    0.16       0
  5235.1    0.07       0
Bank Sta=5007.3,5011.9
Exp/Cntr=0.3,0.1

Type RM Length L Ch R = 1,7539,162,162,162
BEGIN DESCRIPTION:
elmc636
END DESCRIPTION:
XS GIS Cut Line= 3
      1496895.41      6766377.27      1496851.14      6766243.17
      1496796.92      6766021.11
#Sta/Elev= 30
  4861.8 2367.01  4909.7 2364.44  4915.0 2364.63  4924.2 2363.72  4941.4 2362.98
  4946.7 2362.13  4955.8 2359.31  4966.3 2353.81  4973.2 2348.46  4978.4 2346.88
  4985.1 2341.49  4985.4 2340.99  4989.4 2340.99  4989.7 2341.49  4997.8 2342.64
  5003.0 2342.64  5010.7 2343.44  5018.6 2342.72  5028.9 2342.65  5039.2 2345.31
  5047.2 2346.20  5080.4 2347.64  5094.0 2348.65  5121.6 2352.65  5130.5 2354.81
  5135.7 2354.75  5142.2 2356.63  5183.3 2360.33  5196.2 2362.34  5231.6 2363.94
#Mann=4,-1,0
  4861.8    0.16       0  4985.1    0.07       0  4989.7    0.16       0
  5196.2    0.07       0
Bank Sta=4985.1,4989.7
Exp/Cntr=0.3,0.1

Type RM Length L Ch R = 1,7377,216,216,216
BEGIN DESCRIPTION:
elmc635
END DESCRIPTION:
XS GIS Cut Line= 3
      1497043.86      6766347.36      1496995.67      6766180.67
      1496969.82      6765927.30
#Sta/Elev= 30
  4830.2 2365.74  4839.4 2365.20  4844.6 2365.39  4860.8 2364.49  4871.2 2364.64
  4883.4 2363.96  4902.4 2362.24  4917.1 2361.69  4923.2 2360.58  4944.0 2358.18
  4950.7 2355.43  4955.9 2353.82  4975.3 2345.40  4984.3 2340.59  4987.2 2339.52
  4987.5 2339.02  4991.5 2339.02  4991.8 2339.52  5016.4 2340.76  5026.5 2342.69
  5036.5 2343.51  5086.8 2346.02  5106.9 2349.16  5117.0 2350.12  5147.1 2353.86
  5167.2 2356.75  5187.3 2358.50  5223.4 2360.98  5247.6 2362.20  5258.4 2363.18
#Mann=4,-1,0
  4830.2    0.16       0  4987.2    0.07       0  4991.8    0.16       0
  5223.4    0.07       0
Bank Sta=4987.2,4991.8
Exp/Cntr=0.3,0.1

Type RM Length L Ch R = 1,7161,152,152,152
BEGIN DESCRIPTION:
elmc634
END DESCRIPTION:
XS GIS Cut Line= 3
      1497243.08      6766258.81      1497187.08      6766109.06
      1497137.61      6765859.09
#Sta/Elev= 30
  4836.2 2361.64  4849.0 2361.67  4858.4 2360.81  4868.6 2360.39  4874.0 2360.70
  4898.9 2359.24  4904.3 2359.71  4929.2 2357.27  4934.6 2357.38  4954.2 2353.43
  4959.5 2352.82  4965.2 2349.37  4984.5 2342.82  4989.8 2342.03  4994.0 2339.19
  5005.0 2338.92  5005.4 2338.42  5009.4 2338.42  5009.7 2338.92  5032.7 2339.61
  5048.1 2341.67  5068.5 2343.08  5129.7 2346.05  5150.1 2349.53  5170.5 2354.05
  5180.7 2355.50  5186.4 2357.66  5211.2 2360.55  5241.1 2362.97  5250.9 2363.92
#Mann=4,-1,0
  4836.2    0.16       0  5005.0    0.07       0  5009.7    0.16       0
  5241.1   0.035       0
Bank Sta=5005,5009.7
Exp/Cntr=0.3,0.1

Type RM Length L Ch R = 1,7009,106,106,106
BEGIN DESCRIPTION:
elmc633
END DESCRIPTION:
XS GIS Cut Line= 3
      1497280.84      6766263.97      1497313.38      6766036.14
      1497279.76      6765796.94
#Sta/Elev= 30
  4761.4 2361.20  4767.4 2360.39  4787.6 2359.33  4829.6 2357.69  4868.4 2354.52
  4888.7 2350.78  4895.3 2348.07  4900.4 2347.29  4908.9 2344.98  4919.0 2343.61
  4949.3 2341.66  4966.0 2337.99  4991.5 2338.91  4997.4 2335.95  4997.8 2335.45
  5001.8 2335.45  5002.1 2335.95  5009.9 2336.12  5015.4 2337.90  5030.1 2340.17
  5060.4 2342.70  5080.6 2345.92  5086.7 2347.73  5091.7 2347.47  5131.0 2355.95
  5152.2 2359.27  5157.9 2360.50  5171.4 2361.45  5181.5 2363.09  5233.1 2369.39
#Mann=4,-1,0
  4761.4    0.16       0  4997.4    0.07       0  5002.1    0.16       0
  5152.2   0.035       0
Bank Sta=4997.4,5002.1
Exp/Cntr=0.3,0.1

Type RM Length L Ch R = 1,6903,157,157,157
BEGIN DESCRIPTION:
elmc632
END DESCRIPTION:
XS GIS Cut Line= 3
      1497286.03      6766264.03      1497403.23      6766020.51
      1497412.31      6765792.15
#Sta/Elev= 30
  4696.8 2361.20  4714.6 2358.91  4747.2 2357.94  4759.0 2356.49  4769.8 2356.21
  4775.4 2355.15  4792.3 2354.74  4814.5 2350.75  4820.6 2349.02  4865.9 2343.01
  4881.1 2342.48  4888.5 2341.50  4894.1 2341.96  4947.6 2340.83  4956.4 2338.87
  4962.0 2339.33  4965.7 2337.76  4970.8 2337.76  4997.2 2334.73  4997.6 2334.23
  5001.9 2334.73  5009.6 2334.74  5019.6 2336.55  5039.6 2343.27  5096.7 2356.50
  5119.7 2360.85  5129.7 2361.54  5159.7 2366.41  5189.7 2370.11  5195.6 2372.46
#Mann=4,-1,0
  4696.8    0.16       0  4997.2    0.07       0  5001.9    0.16       0
  5096.7   0.035       0
Bank Sta=4997.2,5001.9
Exp/Cntr=0.3,0.1