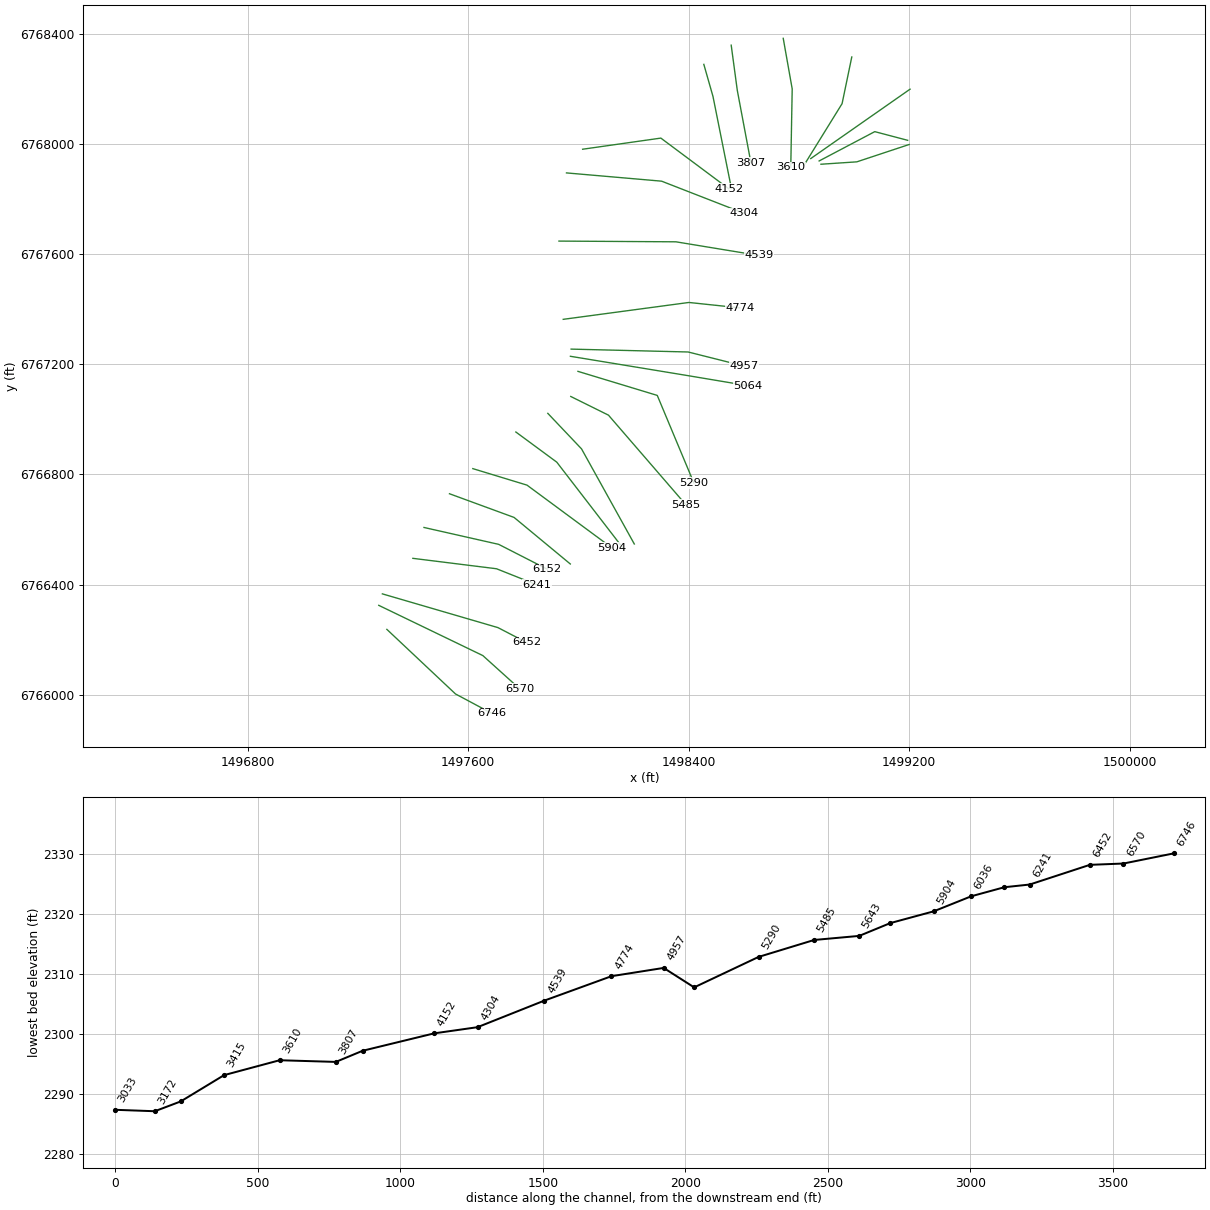
HEC-RAS study Elm 31.prj: Elm 31 Base Level Engineering

--- Elm 31.g01 (geometry) --- (continued)

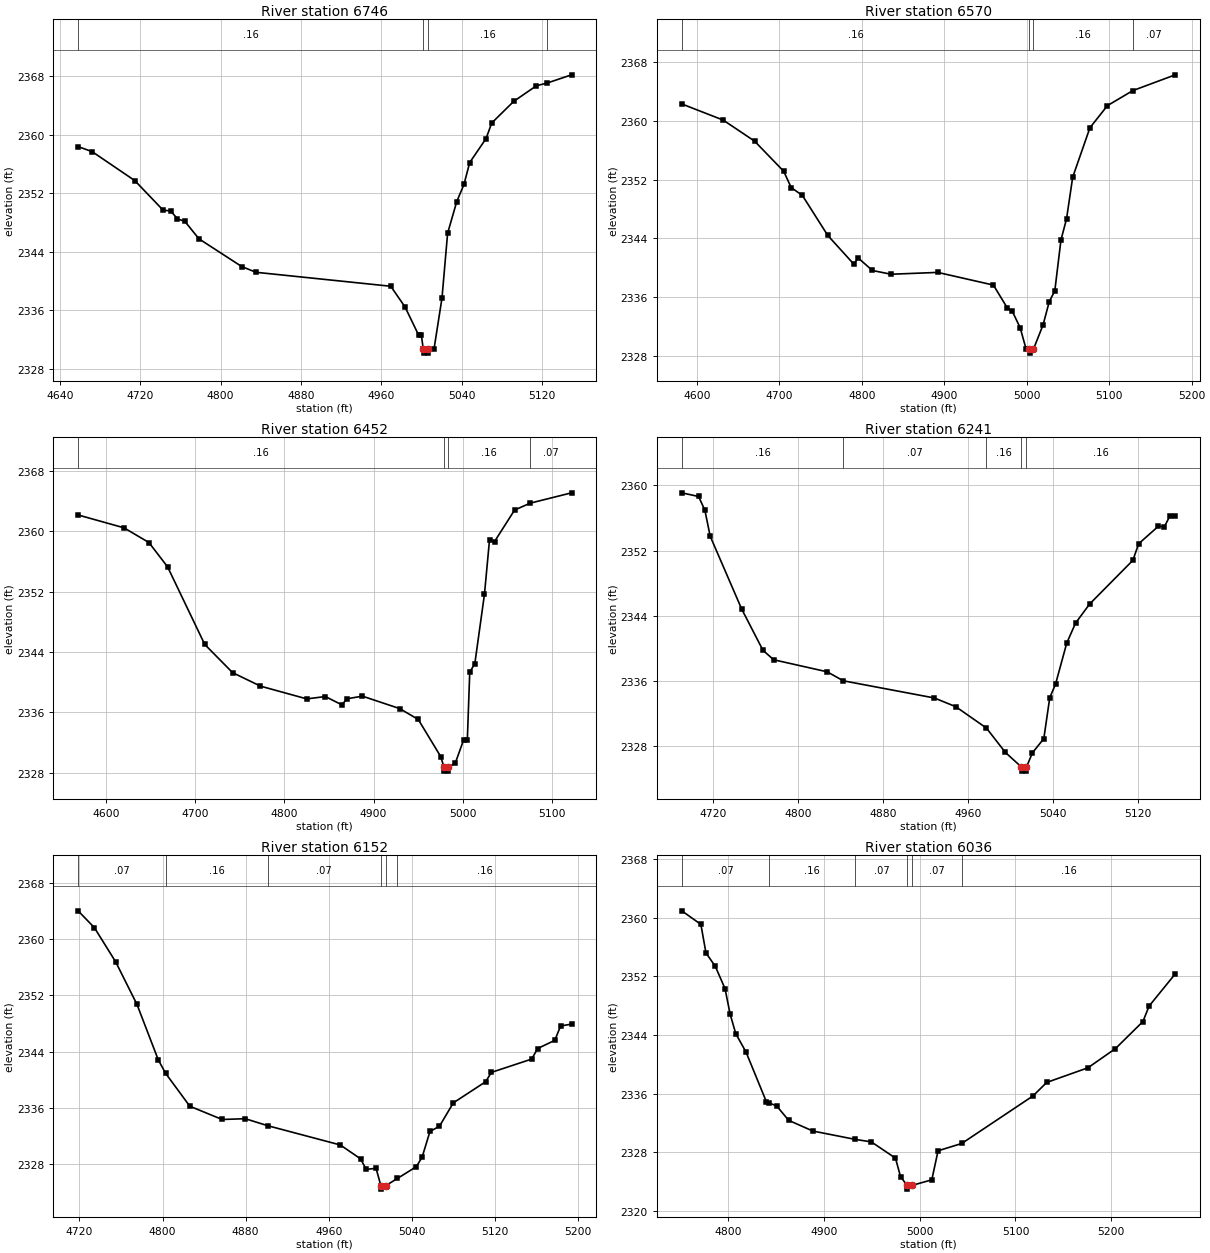
Type RM Length L Ch R = 1,6746,176,176,176
BEGIN DESCRIPTION:
elmc358
END DESCRIPTION:
XS GIS Cut Line= 3
      1497304.97      6766238.03      1497553.97      6766003.74
      1497685.81      6765933.26
#Sta/Elev= 30
  4658.1 2358.37  4672.1 2357.68  4714.6 2353.72  4742.9 2349.66  4750.2 2349.59
  4757.1 2348.49  4764.4 2348.15  4778.5 2345.76  4821.0 2341.98  4835.2 2341.19
  4969.5 2339.28  4983.7 2336.45  4997.3 2332.59  5000.0 2332.59  5001.9 2330.64
  5002.2 2330.14  5006.2 2330.14  5006.6 2330.64  5012.5 2330.64  5020.5 2337.66
  5026.1 2346.52  5035.2 2350.85  5042.4 2353.20  5048.1 2356.19  5064.4 2359.47
  5070.0 2361.59  5092.0 2364.56  5114.6 2366.69  5125.1 2367.05  5149.5 2368.18
#Mann=4,-1,0
  4658.1    0.16       0  5001.9    0.07       0  5006.6    0.16       0
  5125.1   0.035       0
Bank Sta=5001.9,5006.6
Exp/Cntr=0.3,0.1

Type RM Length L Ch R = 1,6570,118,118,118
BEGIN DESCRIPTION:
elmc631
END DESCRIPTION:
XS GIS Cut Line= 3
      1497275.59      6766325.22      1497653.23      6766142.91
      1497786.04      6766023.11
#Sta/Elev= 30
  4581.8 2362.25  4632.0 2360.06  4670.0 2357.21  4705.4 2353.11  4714.4 2350.91
  4728.0 2349.84  4758.8 2344.41  4790.2 2340.54  4795.8 2341.34  4812.9 2339.66
  4835.5 2339.15  4892.1 2339.40  4959.6 2337.68  4976.6 2334.55  4982.2 2334.19
  4992.0 2331.90  4999.2 2329.01  5003.3 2328.95  5003.7 2328.45  5008.0 2328.95
  5019.8 2332.28  5027.3 2335.44  5034.0 2336.89  5041.5 2343.81  5048.2 2346.64
  5055.7 2352.31  5076.6 2359.02  5097.8 2362.02  5128.6 2364.06  5180.0 2366.20
#Mann=4,-1,0
  4581.8    0.16       0  5003.3    0.07       0  5008.0    0.16       0
  5128.6    0.07       0
Bank Sta=5003.3,5008
Exp/Cntr=0.3,0.1

Type RM Length L Ch R = 1,6452,211,211,211
BEGIN DESCRIPTION:
elmc630
END DESCRIPTION:
XS GIS Cut Line= 3
      1497288.64      6766366.87      1497707.91      6766244.47
      1497811.72      6766190.65
#Sta/Elev= 30
  4568.4 2362.13  4619.9 2360.43  4647.9 2358.48  4668.8 2355.27  4710.5 2345.00
  4741.7 2341.27  4773.0 2339.48  4825.0 2337.79  4845.9 2338.10  4864.6 2336.99
  4869.8 2337.80  4887.5 2338.15  4929.2 2336.51  4950.1 2335.07  4975.4 2330.14
  4979.0 2328.73  4979.3 2328.23  4983.3 2328.23  4983.7 2328.73  4991.7 2329.30
  5001.1 2332.38  5005.2 2332.38  5007.9 2341.32  5013.6 2342.46  5024.4 2351.62
  5030.1 2358.86  5035.7 2358.61  5058.2 2362.78  5075.7 2363.69  5122.1 2365.06
#Mann=4,-1,0
  4568.4    0.16       0  4979.0    0.07       0  4983.7    0.16       0
  5075.7    0.07       0
Bank Sta=4979,4983.7
Exp/Cntr=0.3,0.1

Type RM Length L Ch R = 1,6241,89,89,89
BEGIN DESCRIPTION:
elmc625
END DESCRIPTION:
XS GIS Cut Line= 3
      1497399.28      6766495.78      1497702.71      6766458.01
      1497849.80      6766399.44
#Sta/Elev= 30
  4690.7 2359.10  4706.5 2358.65  4712.4 2356.97  4717.4 2353.78  4746.9 2344.87
  4767.0 2339.78  4777.1 2338.61  4827.5 2337.13  4842.5 2336.03  4928.2 2333.92
  4948.4 2332.85  4977.2 2330.23  4995.1 2327.23  5010.2 2325.44  5010.6 2324.94
  5014.6 2324.94  5014.9 2325.44  5020.5 2327.19  5031.2 2328.93  5036.8 2333.96
  5042.2 2335.60  5052.8 2340.67  5061.1 2343.12  5074.3 2345.45  5115.0 2350.82
  5120.4 2352.85  5138.9 2354.99  5144.7 2354.96  5150.0 2356.31  5154.8 2356.31
#Mann=5,-1,0
  4690.7    0.16       0  4842.5    0.07       0  4977.2    0.16       0
  5010.2    0.07       0  5014.9    0.16       0
Bank Sta=5010.2,5014.9
Exp/Cntr=0.3,0.1

Type RM Length L Ch R = 1,6152,116,116,116
BEGIN DESCRIPTION:
elmc626
END DESCRIPTION:
XS GIS Cut Line= 3
      1497439.70      6766607.75      1497710.52      6766546.56
      1497886.34      6766456.69
#Sta/Elev= 30
  4718.7 2364.01  4734.4 2361.62  4754.9 2356.76  4775.4 2350.72  4795.9 2342.85
  4802.9 2340.95  4826.3 2336.26  4857.4 2334.38  4879.7 2334.49  4901.2 2333.50
  4971.2 2330.76  4990.7 2328.79  4996.1 2327.29  5005.6 2327.45  5010.2 2324.99
  5010.6 2324.49  5015.0 2324.99  5026.1 2326.00  5044.4 2327.68  5050.0 2329.05
  5057.5 2332.68  5066.6 2333.41  5080.0 2336.74  5111.0 2339.73  5116.7 2341.07
  5155.5 2342.96  5161.1 2344.45  5177.7 2345.62  5183.3 2347.66  5193.8 2347.92
#Mann=6,-1,0
  4718.7    0.07       0  4802.9    0.16       0  4901.2    0.07       0
  5010.2    0.07       0  5015.0    0.07       0  5026.1    0.16       0
Bank Sta=5010.2,5015
Exp/Cntr=0.3,0.1

Type RM Length L Ch R = 1,6036,132,132,132
BEGIN DESCRIPTION:
elmc627
END DESCRIPTION:
XS GIS Cut Line= 3
      1497532.12      6766730.15      1497766.51      6766644.21
      1497970.51      6766475.30
#Sta/Elev= 30
  4752.1 2360.96  4772.0 2359.11  4777.3 2355.22  4787.1 2353.37  4797.2 2350.33
  4802.5 2346.86  4808.4 2344.19  4819.1 2341.68  4840.4 2334.87  4843.3 2334.73
  4851.0 2334.34  4863.5 2332.37  4888.7 2330.91  4933.2 2329.76  4949.7 2329.43
  4974.9 2327.21  4980.2 2324.68  4987.1 2323.48  4987.4 2322.98  4991.9 2323.48
  5012.8 2324.25  5019.3 2328.21  5044.0 2329.21  5118.3 2335.70  5132.6 2337.54
  5175.6 2339.54  5204.3 2342.16  5232.9 2345.85  5239.4 2347.97  5266.6 2352.35
#Mann=6,-1,0
  4752.1    0.07       0  4843.3    0.16       0  4933.2    0.07       0
  4987.1    0.07       0  4991.9    0.07       0  5044.0    0.16       0
Bank Sta=4987.1,4991.9
Exp/Cntr=0.3,0.1

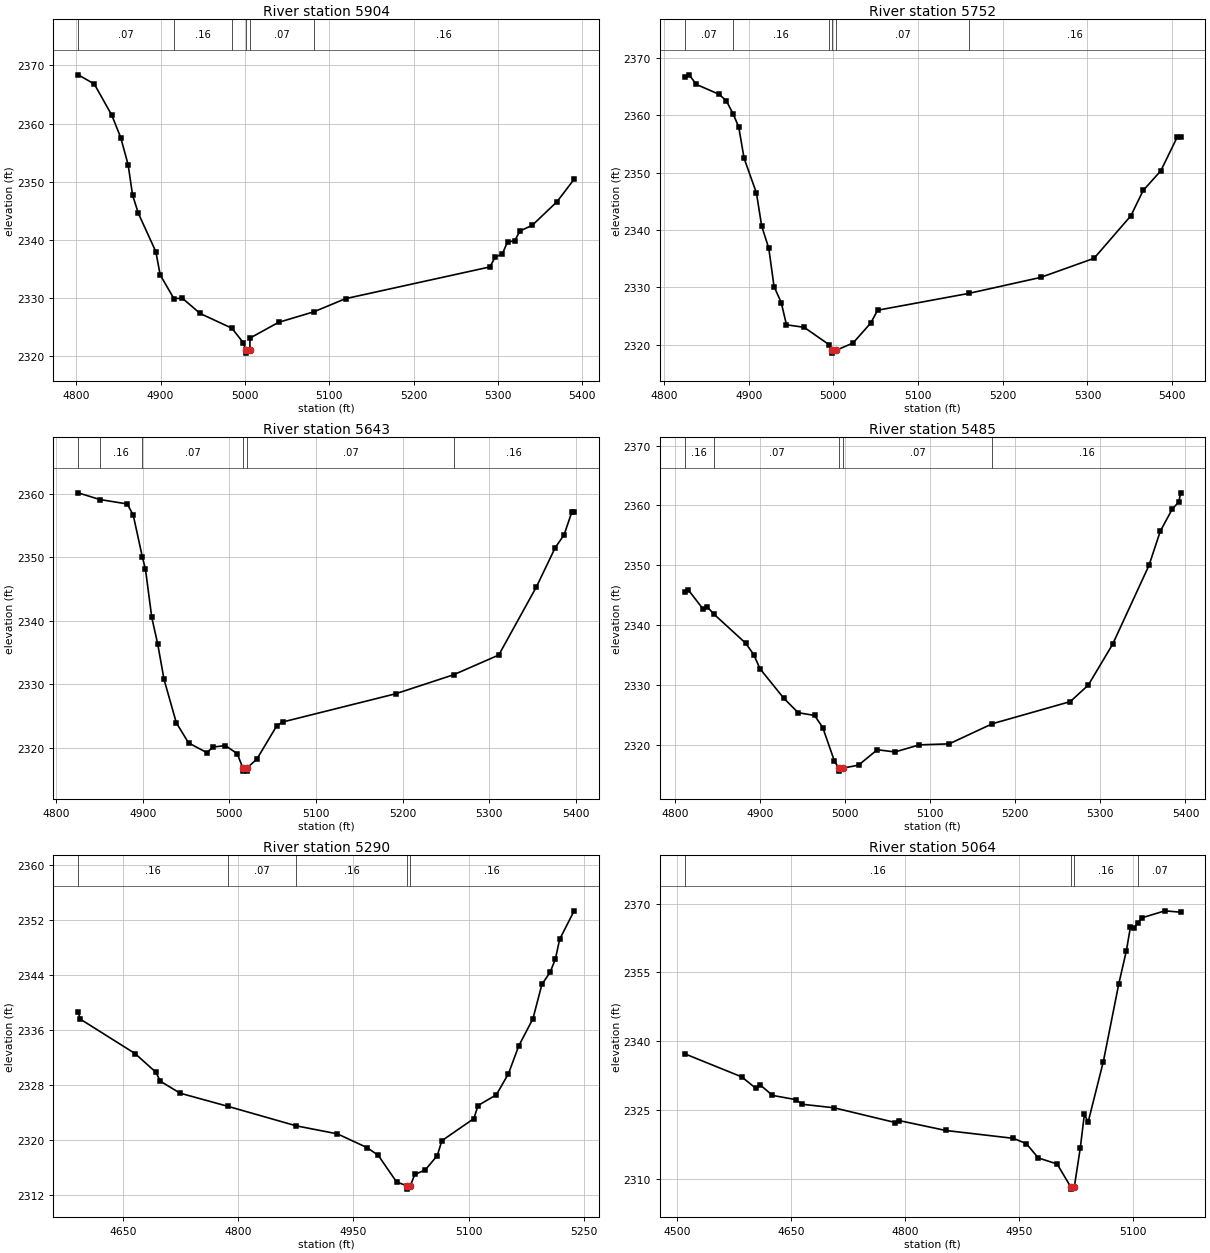
Type RM Length L Ch R = 1,5904,152,152,152
BEGIN DESCRIPTION:
elmc628
END DESCRIPTION:
XS GIS Cut Line= 3
      1497616.81      6766821.28      1497813.38      6766761.40
      1498121.01      6766534.25
#Sta/Elev= 30
  4802.4 2368.39  4821.4 2366.82  4842.3 2361.41  4852.8 2357.58  4861.6 2352.89
  4866.8 2347.70  4873.7 2344.53  4894.4 2337.94  4899.6 2333.92  4915.8 2329.86
  4926.0 2329.90  4946.9 2327.29  4984.6 2324.75  4998.2 2322.23  5001.0 2320.96
  5001.3 2320.46  5005.8 2320.96  5006.1 2323.06  5039.9 2325.76  5081.8 2327.58
  5119.3 2329.84  5290.5 2335.31  5296.7 2337.00  5305.1 2337.52  5311.3 2339.61
  5319.8 2339.80  5326.0 2341.49  5340.6 2342.47  5369.9 2346.53  5390.3 2350.41
#Mann=6,-1,0
  4802.4    0.07       0  4915.8    0.16       0  4984.6    0.07       0
  5001.0    0.07       0  5005.8    0.07       0  5081.8    0.16       0
Bank Sta=5001,5005.8
Exp/Cntr=0.3,0.1

Type RM Length L Ch R = 1,5752,109,109,109
BEGIN DESCRIPTION:
elmc629
END DESCRIPTION:
XS GIS Cut Line= 3
      1497773.00      6766954.12      1497921.46      6766844.73
      1498166.26      6766527.01
#Sta/Elev= 30
  4824.5 2366.67  4829.8 2367.08  4838.2 2365.41  4865.3 2363.67  4873.7 2362.54
  4881.7 2360.25  4888.3 2357.98  4894.6 2352.53  4909.2 2346.46  4915.4 2340.69
  4923.8 2336.79  4930.0 2330.12  4938.5 2327.32  4944.7 2323.44  4965.5 2323.01
  4995.0 2319.97  4998.6 2319.00  4999.0 2318.50  5003.4 2319.00  5023.3 2320.27
  5044.1 2323.74  5052.3 2325.99  5159.7 2328.92  5244.6 2331.71  5307.8 2335.05
  5351.3 2342.48  5365.8 2346.90  5386.6 2350.32  5406.2 2356.28  5410.0 2356.28
#Mann=6,-1,0
  4824.5    0.07       0  4881.7    0.16       0  4995.0    0.07       0
  4998.6    0.07       0  5003.4    0.07       0  5159.7    0.16       0
Bank Sta=4998.6,5003.4
Exp/Cntr=0.3,0.1

Type RM Length L Ch R = 1,5643,158,158,158
BEGIN DESCRIPTION:
elmc624
END DESCRIPTION:
XS GIS Cut Line= 3
      1497888.93      6767021.79      1498011.30      6766892.91
      1498202.71      6766547.86
#Sta/Elev= 30
  4825.5 2360.11  4850.3 2359.06  4882.1 2358.36  4889.0 2356.61  4899.4 2350.10
  4903.1 2348.09  4910.4 2340.52  4917.3 2336.30  4924.5 2330.80  4938.7 2323.96
  4952.8 2320.80  4973.9 2319.27  4981.2 2320.15  4995.3 2320.37  5008.9 2319.12
  5015.5 2316.86  5015.8 2316.36  5019.9 2316.36  5020.3 2316.86  5031.7 2318.26
  5054.6 2323.48  5061.3 2324.08  5191.8 2328.52  5258.7 2331.51  5310.8 2334.61
  5354.3 2345.34  5376.0 2351.50  5386.2 2353.51  5395.0 2357.05  5397.8 2357.05
#Mann=6,-1,0
  4825.5    0.07       0  4850.3    0.16       0  4899.4    0.07       0
  5015.5    0.07       0  5020.3    0.07       0  5258.7    0.16       0
Bank Sta=5015.5,5020.3
Exp/Cntr=0.3,0.1

Type RM Length L Ch R = 1,5485,195,195,195
BEGIN DESCRIPTION:
elmc623
END DESCRIPTION:
XS GIS Cut Line= 3
      1497972.22      6767083.02      1498108.96      6767015.31
      1498390.09      6766689.92
#Sta/Elev= 30
  4811.7 2345.53  4816.1 2345.89  4832.9 2342.80  4838.5 2343.03  4846.2 2341.85
  4883.3 2337.03  4892.9 2335.10  4900.2 2332.75  4928.2 2327.83  4945.0 2325.43
  4964.3 2324.97  4973.9 2322.95  4987.5 2317.40  4992.7 2316.18  4993.1 2315.68
  4997.5 2316.18  5016.0 2316.68  5037.9 2319.25  5058.8 2318.88  5087.3 2320.06
  5122.4 2320.23  5173.2 2323.59  5264.7 2327.28  5285.8 2330.03  5314.3 2336.81
  5357.1 2349.99  5370.4 2355.70  5384.6 2359.44  5392.2 2360.58  5394.3 2362.11
#Mann=5,-1,0
  4811.7    0.16       0  4846.2    0.07       0  4992.7    0.07       0
  4997.5    0.07       0  5173.2    0.16       0
Bank Sta=4992.7,4997.5
Exp/Cntr=0.3,0.1

Type RM Length L Ch R = 1,5290,226,226,226
BEGIN DESCRIPTION:
elmc622
END DESCRIPTION:
XS GIS Cut Line= 3
      1497998.31      6767174.15      1498286.04      6767086.92
      1498418.85      6766769.22
#Sta/Elev= 30
  4592.0 2338.58  4594.9 2337.60  4665.9 2332.60  4693.0 2329.88  4698.8 2328.57
  4724.4 2326.83  4787.3 2324.89  4875.5 2322.07  4929.1 2320.90  4967.4 2318.91
  4982.2 2317.78  5006.0 2313.90  5019.1 2313.35  5019.5 2312.85  5023.9 2313.35
  5029.8 2314.99  5043.2 2315.63  5059.0 2317.73  5064.9 2319.90  5106.6 2323.13
  5112.0 2325.03  5135.8 2326.59  5151.6 2329.68  5165.0 2333.73  5183.4 2337.67
  5195.0 2342.66  5205.8 2344.46  5212.6 2346.37  5218.1 2349.23  5237.0 2353.39
#Mann=5,-1,0
  4592.0    0.16       0  4787.3    0.07       0  4875.5    0.16       0
  5019.1    0.07       0  5023.9    0.16       0
Bank Sta=5019.1,5023.9
Exp/Cntr=0.3,0.1

Type RM Length L Ch R = 1,5064,107,107,107
BEGIN DESCRIPTION:
elmc621
END DESCRIPTION:
XS GIS Cut Line= 3
      1497970.91      6767228.85      1498398.02      6767158.54
      1498615.43      6767122.08
#Sta/Elev= 30
  4509.9 2337.26  4585.0 2332.23  4603.8 2329.71  4608.9 2330.55  4625.5 2328.19
  4655.9 2327.28  4665.0 2326.25  4706.6 2325.49  4787.4 2322.27  4792.5 2322.70
  4853.6 2320.55  4942.8 2318.83  4960.0 2317.67  4975.7 2314.56  5000.5 2313.24
  5018.4 2308.26  5018.8 2307.76  5023.2 2308.26  5031.0 2316.69  5036.4 2324.03
  5041.4 2322.39  5061.4 2335.56  5081.7 2352.46  5091.8 2359.77  5097.0 2364.80
  5102.1 2364.72  5107.4 2365.87  5112.1 2366.89  5142.5 2368.42  5163.2 2368.12
#Mann=4,-1,0
  4509.9    0.16       0  5018.4    0.07       0  5023.2    0.16       0
  5107.4    0.07       0
Bank Sta=5018.4,5023.2
Exp/Cntr=0.3,0.1

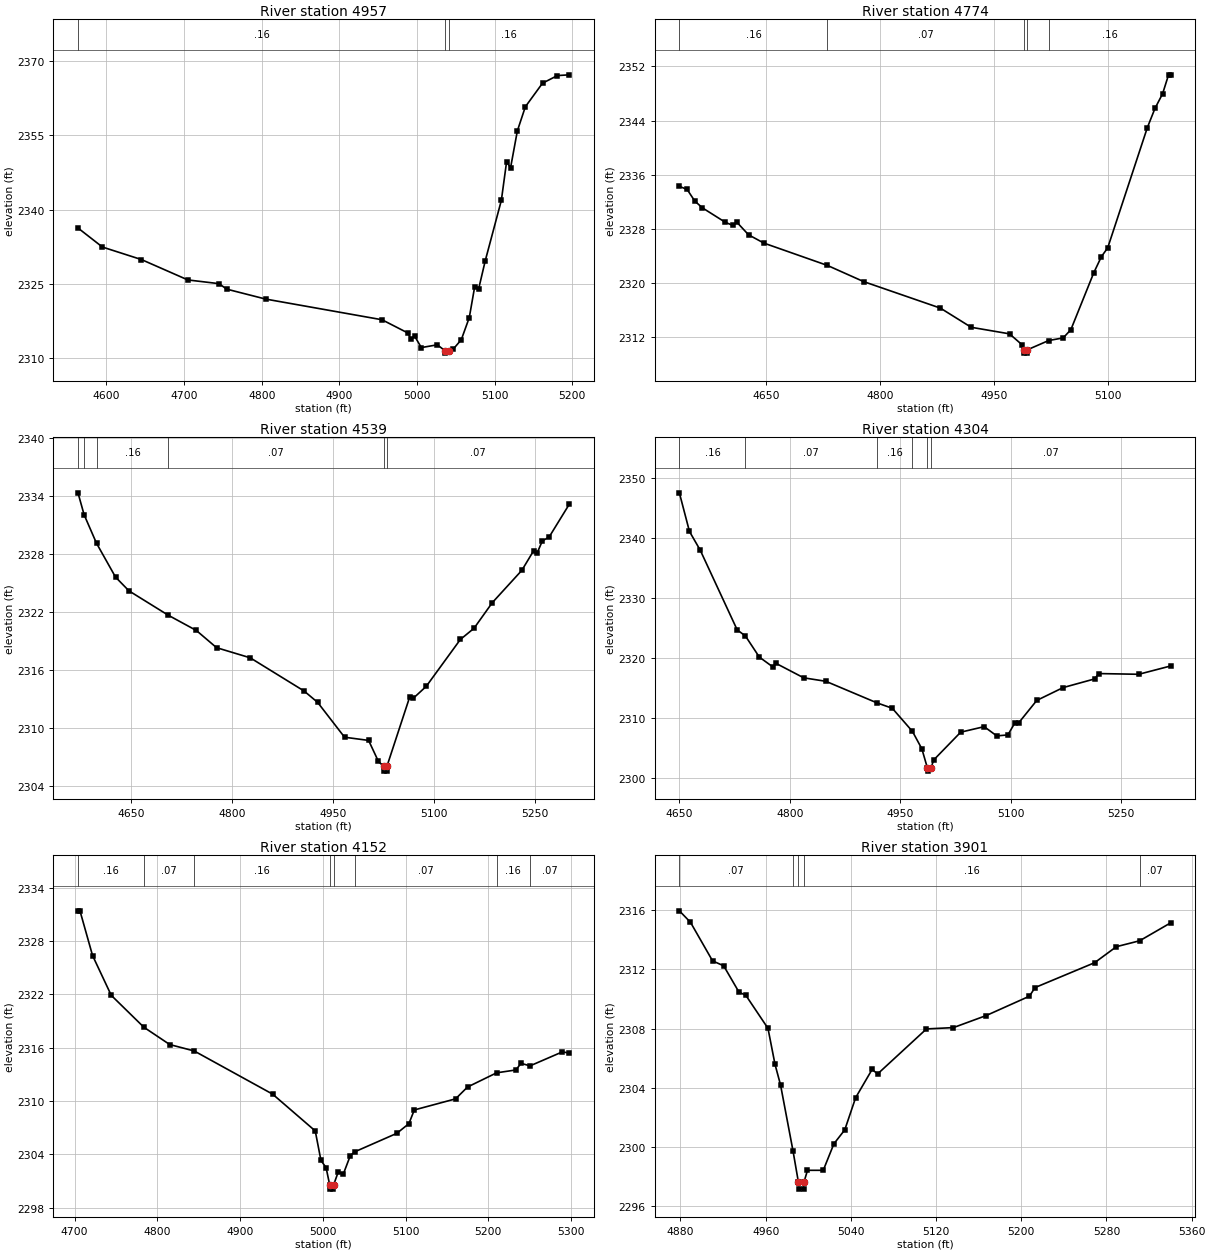
Type RM Length L Ch R = 1,4957,183,183,183
BEGIN DESCRIPTION:
elmc620
END DESCRIPTION:
XS GIS Cut Line= 3
      1497973.50      6767254.89      1498398.02      6767244.47
      1498599.88      6767193.68
#Sta/Elev= 30
  4563.3 2336.28  4594.8 2332.43  4645.1 2329.90  4704.8 2325.79  4744.9 2325.04
  4754.9 2323.93  4804.9 2321.93  4954.9 2317.75  4987.9 2315.10  4992.0 2313.95
  4997.1 2314.39  5005.5 2312.13  5026.1 2312.69  5035.9 2311.51  5036.2 2311.01
  5040.7 2311.51  5046.7 2311.84  5057.0 2313.72  5067.3 2318.20  5074.2 2324.39
  5079.4 2324.02  5087.9 2329.70  5108.6 2341.87  5115.3 2349.62  5120.5 2348.48
  5129.2 2355.89  5139.5 2360.76  5161.6 2365.52  5180.8 2367.06  5196.1 2367.21
#Mann=3,-1,0
  4563.3    0.16       0  5035.9    0.07       0  5040.7    0.16       0
Bank Sta=5035.9,5040.7
Exp/Cntr=0.3,0.1

Type RM Length L Ch R = 1,4774,235,235,235
BEGIN DESCRIPTION:
elmc619
END DESCRIPTION:
XS GIS Cut Line= 3
      1497944.92      6767362.97      1498400.62      6767424.16
      1498585.50      6767404.63
#Sta/Elev= 30
  4536.2 2334.28  4546.4 2333.82  4556.5 2332.10  4566.5 2331.10  4596.8 2328.95
  4606.7 2328.50  4611.8 2328.97  4627.1 2327.12  4647.3 2325.89  4730.8 2322.59
  4778.4 2320.20  4879.3 2316.28  4919.7 2313.45  4970.1 2312.48  4986.3 2310.89
  4988.9 2310.13  4989.3 2309.63  4993.4 2309.63  4993.7 2310.13  5021.5 2311.49
  5040.6 2311.88  5050.7 2313.09  5080.8 2321.50  5090.9 2323.90  5099.1 2325.18
  5151.2 2342.95  5161.3 2345.81  5171.3 2347.97  5179.1 2350.76  5181.9 2350.76
#Mann=5,-1,0
  4536.2    0.16       0  4730.8    0.07       0  4988.9    0.07       0
  4993.7    0.07       0  5021.5    0.16       0
Bank Sta=4988.9,4993.7
Exp/Cntr=0.3,0.1

Type RM Length L Ch R = 1,4539,235,235,235
BEGIN DESCRIPTION:
elmc618
END DESCRIPTION:
XS GIS Cut Line= 3
      1497929.26      6767646.82      1498353.75      6767644.21
      1498654.51      6767594.74
#Sta/Elev= 30
  4571.1 2334.37  4580.2 2332.10  4598.6 2329.15  4626.8 2325.65  4646.8 2324.22
  4705.1 2321.70  4746.8 2320.12  4776.8 2318.34  4826.8 2317.29  4906.8 2313.85
  4926.8 2312.68  4966.8 2309.07  5002.5 2308.74  5017.1 2306.56  5024.8 2306.06
  5025.2 2305.56  5029.4 2305.56  5029.7 2306.06  5063.7 2313.28  5068.8 2313.10
  5088.1 2314.34  5138.7 2319.19  5159.0 2320.35  5186.1 2323.00  5230.0 2326.35
  5247.3 2328.36  5252.4 2328.10  5260.4 2329.39  5270.5 2329.80  5300.4 2333.19
#Mann=6,-1,0
  4571.1    0.16       0  4580.2    0.07       0  4598.6    0.16       0
  4705.1    0.07       0  5024.8    0.07       0  5029.7    0.07       0
Bank Sta=5024.8,5029.7
Exp/Cntr=0.3,0.1

Type RM Length L Ch R = 1,4304,152,152,152
BEGIN DESCRIPTION:
elmc617
END DESCRIPTION:
XS GIS Cut Line= 3
      1497956.66      6767894.21      1498301.66      6767864.26
      1498601.23      6767747.55
#Sta/Elev= 30
  4649.9 2347.55  4663.6 2341.11  4678.3 2337.97  4728.5 2324.68  4739.7 2323.66
  4758.6 2320.14  4776.6 2318.53  4781.6 2319.07  4818.9 2316.68  4849.0 2316.10
  4918.5 2312.50  4939.3 2311.60  4966.7 2307.74  4979.5 2304.83  4987.1 2301.61
  4987.4 2301.11  4992.0 2301.61  4995.4 2302.95  5032.3 2307.61  5064.2 2308.53
  5081.3 2306.99  5096.4 2307.15  5105.8 2309.13  5111.2 2309.18  5135.7 2312.91
  5171.5 2315.05  5214.4 2316.50  5219.9 2317.39  5274.3 2317.27  5317.7 2318.66
#Mann=6,-1,0
  4649.9    0.16       0  4739.7    0.07       0  4918.5    0.16       0
  4966.7    0.07       0  4987.1    0.07       0  4992.0    0.07       0
Bank Sta=4987.1,4992
Exp/Cntr=0.3,0.1

Type RM Length L Ch R = 1,4152,251,251,251
BEGIN DESCRIPTION:
elmc616
END DESCRIPTION:
XS GIS Cut Line= 3
      1498015.23      6767980.15      1498299.06      6768020.51
      1498545.14      6767836.93
#Sta/Elev= 30
  4704.1 2331.40  4706.5 2331.40  4721.7 2326.37  4744.3 2321.89  4783.7 2318.30
  4815.0 2316.35  4844.5 2315.63  4939.3 2310.77  4990.8 2306.63  4997.7 2303.31
  5003.9 2302.50  5008.2 2300.58  5008.6 2300.08  5012.8 2300.08  5013.1 2300.58
  5018.5 2301.99  5024.7 2301.77  5033.1 2303.83  5038.3 2304.27  5089.4 2306.36
  5104.0 2307.45  5110.5 2308.99  5160.4 2310.24  5174.8 2311.57  5210.0 2313.17
  5233.2 2313.49  5239.5 2314.24  5250.3 2313.95  5289.5 2315.53  5297.8 2315.39
#Mann=8,-1,0
  4704.1    0.16       0  4783.7    0.07       0  4844.5    0.16       0
  5008.2    0.07       0  5013.1    0.16       0  5038.3    0.07       0
  5210.0    0.16       0  5250.3    0.07       0
Bank Sta=5008.2,5013.1
Exp/Cntr=0.3,0.1

Type RM Length L Ch R = 1,3901,94,94,94
BEGIN DESCRIPTION:
elmc357
END DESCRIPTION:
XS GIS Cut Line= 3
      1498454.99      6768288.03      1498488.19      6768171.67
      1498555.00      6767838.00
#Sta/Elev= 30
  4879.0 2315.95  4889.4 2315.18  4910.2 2312.57  4920.6 2312.24  4935.0 2310.46
  4941.4 2310.25  4962.2 2308.02  4968.8 2305.59  4974.0 2304.20  4985.7 2299.75
  4990.7 2297.67  4991.2 2297.17  4995.7 2297.17  4996.1 2297.67  4999.3 2298.44
  5014.1 2298.44  5024.1 2300.23  5034.3 2301.17  5044.5 2303.34  5060.0 2305.25
  5065.1 2304.94  5111.0 2307.98  5136.3 2308.07  5167.0 2308.88  5207.7 2310.19
  5212.9 2310.77  5268.9 2312.45  5289.3 2313.53  5311.2 2313.93  5340.3 2315.14
#Mann=5,-1,0
  4879.0    0.07       0  4985.7    0.16       0  4990.7    0.07       0
  4996.1    0.16       0  5311.2    0.07       0
Bank Sta=4990.7,4996.1
Exp/Cntr=0.3,0.1

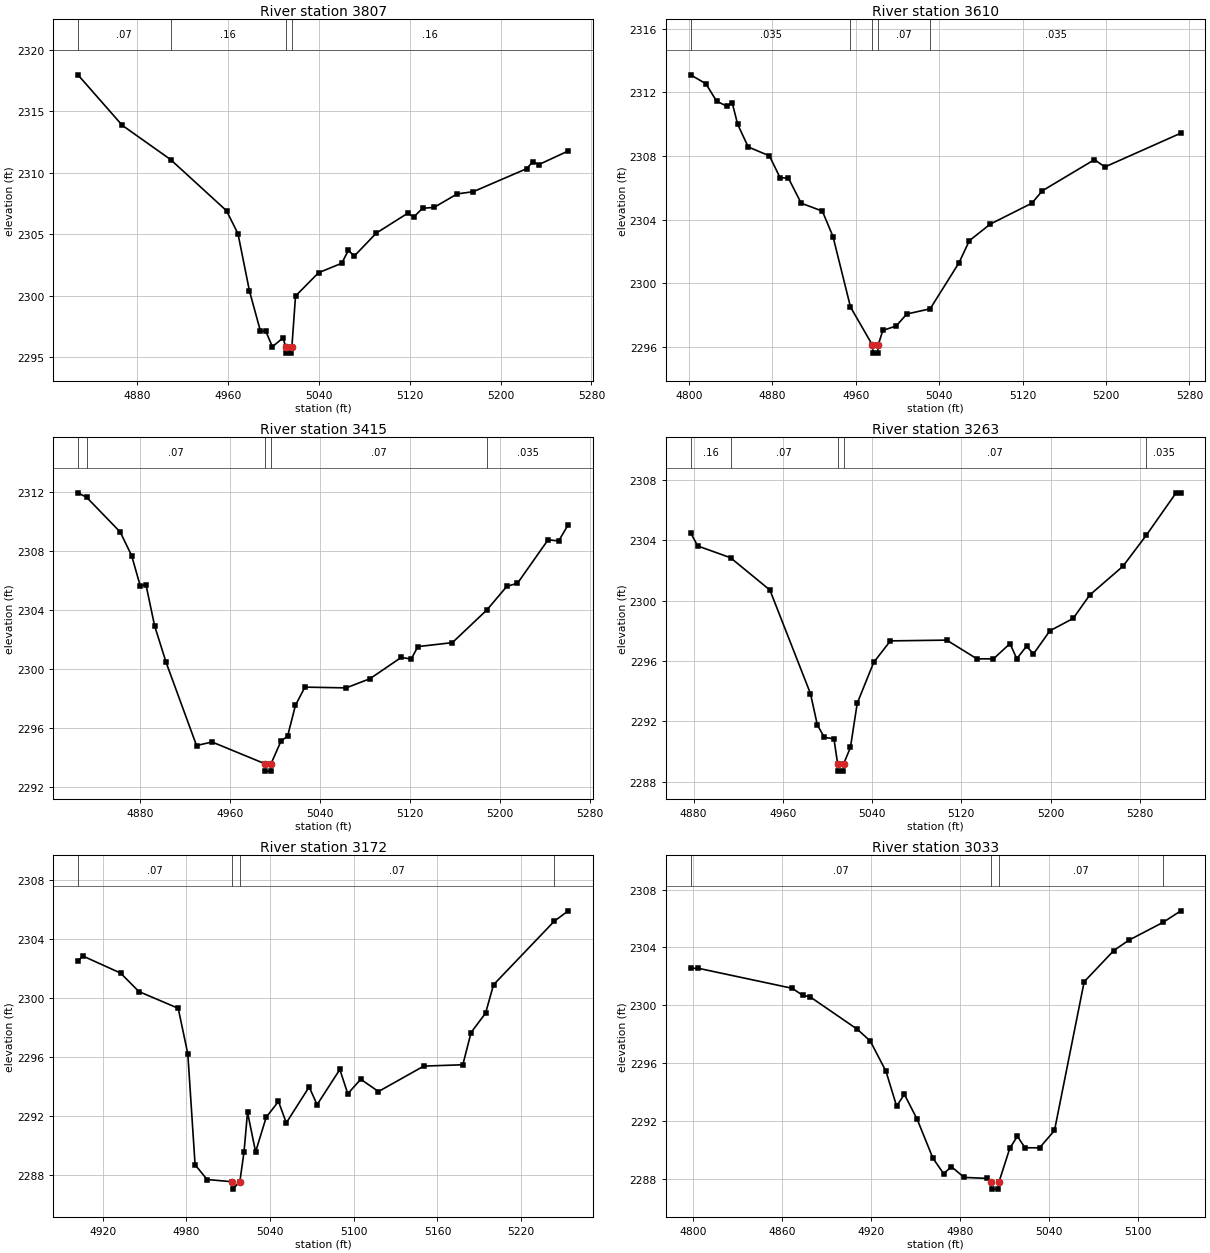
Type RM Length L Ch R = 1,3807,197,197,197
BEGIN DESCRIPTION:
elmc615
END DESCRIPTION:
XS GIS Cut Line= 3
      1498554.27      6768357.74      1498576.40      6768193.69
      1498625.67      6767931.82
#Sta/Elev= 30
  4827.6 2317.98  4866.6 2313.87  4909.2 2311.08  4958.5 2306.91  4968.6 2305.04
  4978.7 2300.38  4988.4 2297.10  4993.1 2297.10  4998.9 2295.83  5008.3 2296.55
  5010.7 2295.81  5011.1 2295.31  5015.6 2295.31  5016.1 2295.81  5019.3 2299.96
  5039.6 2301.86  5060.0 2302.63  5065.9 2303.69  5071.0 2303.21  5090.5 2305.09
  5118.4 2306.72  5123.4 2306.39  5131.2 2307.11  5141.4 2307.18  5161.7 2308.28
  5175.9 2308.46  5222.8 2310.33  5228.4 2310.90  5233.5 2310.66  5259.6 2311.78
#Mann=4,-1,0
  4827.6    0.07       0  4909.2    0.16       0  5010.7    0.07       0
  5016.1    0.16       0
Bank Sta=5010.7,5016.1
Exp/Cntr=0.3,0.1

Type RM Length L Ch R = 1,3610,195,195,195
BEGIN DESCRIPTION:
elmc614
END DESCRIPTION:
XS GIS Cut Line= 3
      1498743.07      6768382.48      1498775.62      6768198.90
      1498770.41      6767915.09
#Sta/Elev= 30
  4801.5 2313.11  4816.2 2312.55  4826.4 2311.46  4836.3 2311.13  4841.4 2311.36
  4846.7 2309.99  4856.8 2308.57  4877.1 2308.01  4887.3 2306.64  4895.4 2306.60
  4907.6 2305.03  4927.9 2304.53  4938.1 2302.93  4954.9 2298.49  4976.0 2296.09
  4976.4 2295.59  4981.0 2295.59  4981.4 2296.09  4985.9 2297.02  4998.8 2297.30
  5008.8 2298.05  5031.3 2298.38  5058.9 2301.27  5068.9 2302.67  5088.9 2303.71
  5128.9 2305.03  5138.9 2305.81  5188.9 2307.77  5198.9 2307.31  5271.8 2309.44
#Mann=5,-1,0
  4801.5   0.035       0  4954.9    0.07       0  4976.0    0.07       0
  4981.4    0.07       0  5031.3   0.035       0
Bank Sta=4976,4981.4
Exp/Cntr=0.3,0.1

Type RM Length L Ch R = 1,3415,152,152,152
BEGIN DESCRIPTION:
elmc613
END DESCRIPTION:
XS GIS Cut Line= 3
      1498991.77      6768314.80      1498956.61      6768145.51
      1498818.11      6767921.59
#Sta/Elev= 30
  4824.6 2311.92  4832.3 2311.62  4862.2 2309.27  4872.4 2307.67  4880.0 2305.63
  4885.1 2305.71  4892.8 2302.93  4903.0 2300.46  4930.1 2294.83  4943.9 2295.07
  4990.9 2293.60  4991.4 2293.10  4996.0 2293.10  4996.4 2293.60  5005.3 2295.14
  5011.1 2295.46  5018.1 2297.55  5026.5 2298.78  5063.2 2298.73  5084.4 2299.35
  5112.2 2300.79  5121.1 2300.68  5127.0 2301.52  5157.7 2301.79  5188.4 2304.00
  5206.2 2305.60  5215.6 2305.80  5242.8 2308.74  5252.3 2308.67  5260.8 2309.77
#Mann=5,-1,0
  4824.6   0.035       0  4832.3    0.07       0  4990.9    0.07       0
  4996.4    0.07       0  5188.4   0.035       0
Bank Sta=4990.9,4996.4
Exp/Cntr=0.3,0.1

Type RM Length L Ch R = 1,3263,91,91,91
BEGIN DESCRIPTION:
elmc612
END DESCRIPTION:
XS GIS Cut Line= 2
      1499203.24      6768198.03      1498842.99      6767946.28
#Sta/Elev= 30
  4877.3 2304.51  4883.7 2303.63  4913.1 2302.85  4948.4 2300.71  4984.8 2293.84
  4990.9 2291.78  4997.2 2290.94  5005.8 2290.86  5009.1 2289.21  5009.6 2288.71
  5014.2 2288.71  5014.6 2289.21  5020.6 2290.28  5026.7 2293.21  5041.5 2295.92
  5056.4 2297.34  5106.9 2297.39  5134.0 2296.15  5148.8 2296.15  5163.6 2297.16
  5169.7 2296.16  5178.5 2296.99  5184.6 2296.47  5199.4 2298.01  5220.3 2298.83
  5235.1 2300.38  5264.8 2302.28  5285.9 2304.35  5312.5 2307.15  5316.8 2307.15
#Mann=5,-1,0
  4877.3    0.16       0  4913.1    0.07       0  5009.1    0.07       0
  5014.6    0.07       0  5285.9   0.035       0
Bank Sta=5009.1,5014.6
Exp/Cntr=0.3,0.1

Type RM Length L Ch R = 1,3172,139,139,139
BEGIN DESCRIPTION:
elmc611
END DESCRIPTION:
XS GIS Cut Line= 3
      1499194.57      6768012.48      1499075.21      6768043.95
      1498873.35      6767937.60
#Sta/Elev= 30
  4902.2 2302.47  4905.6 2302.84  4932.8 2301.68  4945.9 2300.43  4974.1 2299.30
  4981.0 2296.21  4986.2 2288.72  4994.8 2287.72  5012.8 2287.57  5013.2 2287.07
  5018.3 2287.57  5021.3 2289.59  5023.8 2292.27  5029.6 2289.59  5037.2 2291.93
  5046.0 2293.00  5051.6 2291.55  5068.0 2293.98  5073.7 2292.78  5090.0 2295.16
  5095.7 2293.52  5105.0 2294.50  5117.7 2293.67  5150.2 2295.39  5178.2 2295.48
  5184.1 2297.66  5194.5 2298.97  5200.2 2300.89  5243.9 2305.20  5253.8 2305.89
#Mann=4,-1,0
  4902.2    0.07       0  5012.8    0.07       0  5018.3    0.07       0
  5243.9   0.035       0
Bank Sta=5012.8,5018.3
Exp/Cntr=0.3,0.1

Type RM Length L Ch R = 1,3033,100,100,100
BEGIN DESCRIPTION:
elmc610
END DESCRIPTION:
XS GIS Cut Line= 3
      1499200.00      6767997.29      1499010.11      6767934.36
      1498879.94      6767925.68
#Sta/Elev= 30
  4798.2 2302.56  4803.5 2302.56  4866.7 2301.18  4873.7 2300.70  4878.9 2300.58
  4910.6 2298.35  4919.3 2297.54  4929.9 2295.45  4937.1 2293.04  4942.3 2293.86
  4951.0 2292.12  4961.5 2289.46  4968.8 2288.37  4974.0 2288.86  4982.6 2288.12
  4998.2 2288.05  5000.6 2287.81  5001.1 2287.31  5005.7 2287.31  5006.1 2287.81
  5013.4 2290.14  5018.5 2290.96  5023.6 2290.17  5033.4 2290.16  5043.5 2291.36
  5063.5 2301.63  5083.5 2303.79  5093.6 2304.50  5116.6 2305.73  5128.7 2306.53
#Mann=4,-1,0
  4798.2    0.07       0  5000.6    0.07       0  5006.1    0.07       0
  5116.6   0.035       0
Bank Sta=5000.6,5006.1
Exp/Cntr=0.3,0.1