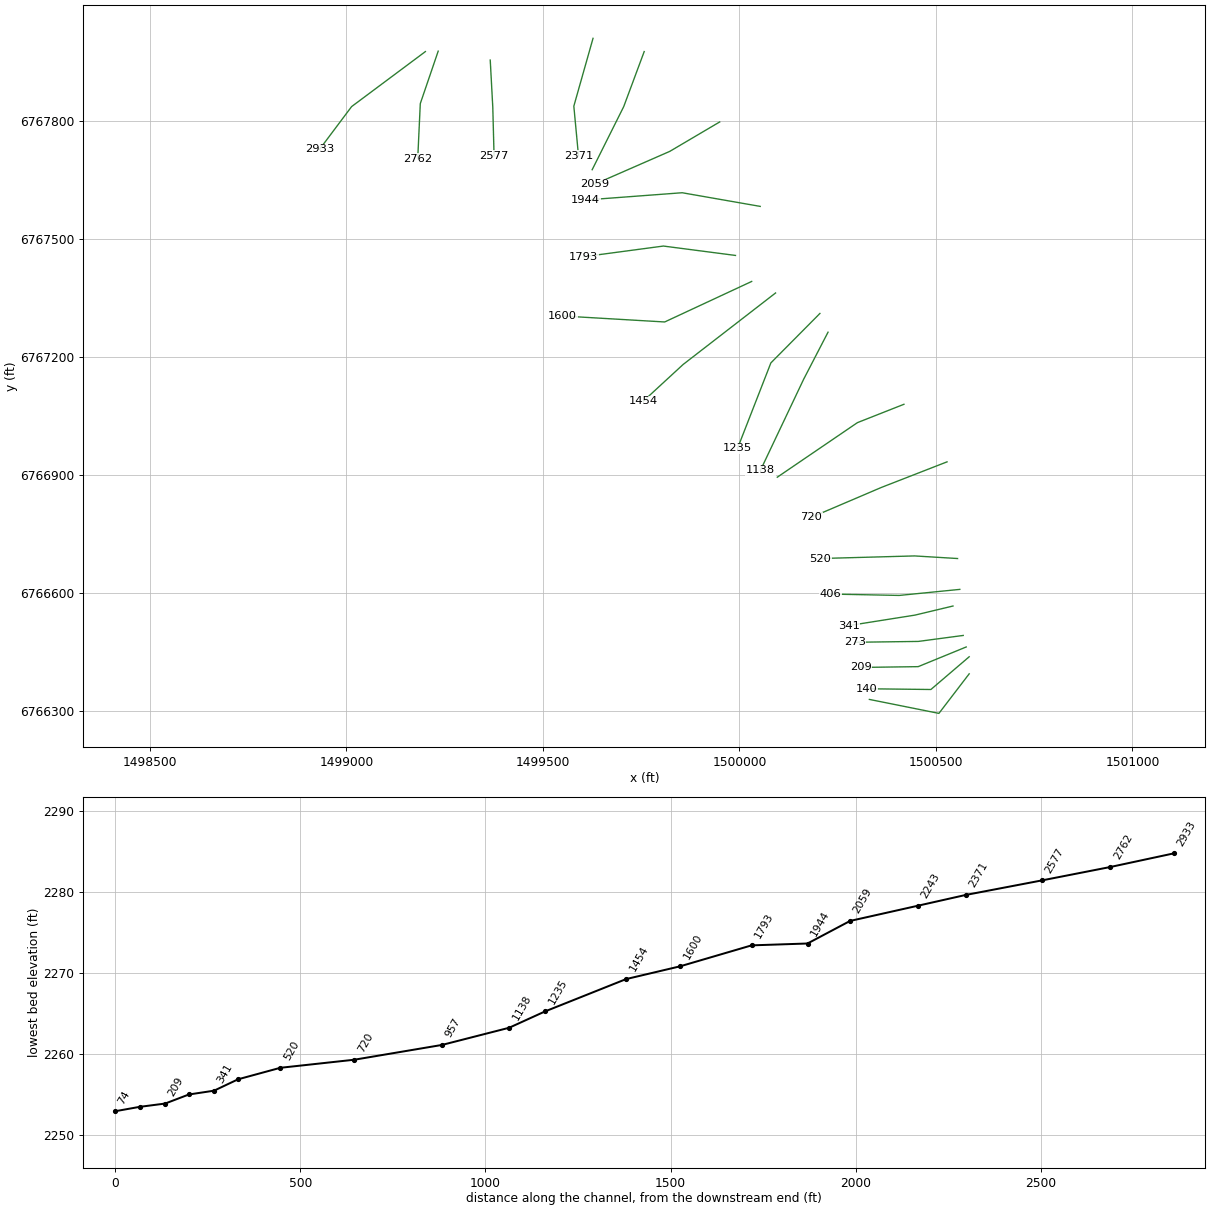
HEC-RAS study Elm 31.prj: Elm 31 Base Level Engineering

--- Elm 31.g01 (geometry) --- (continued)

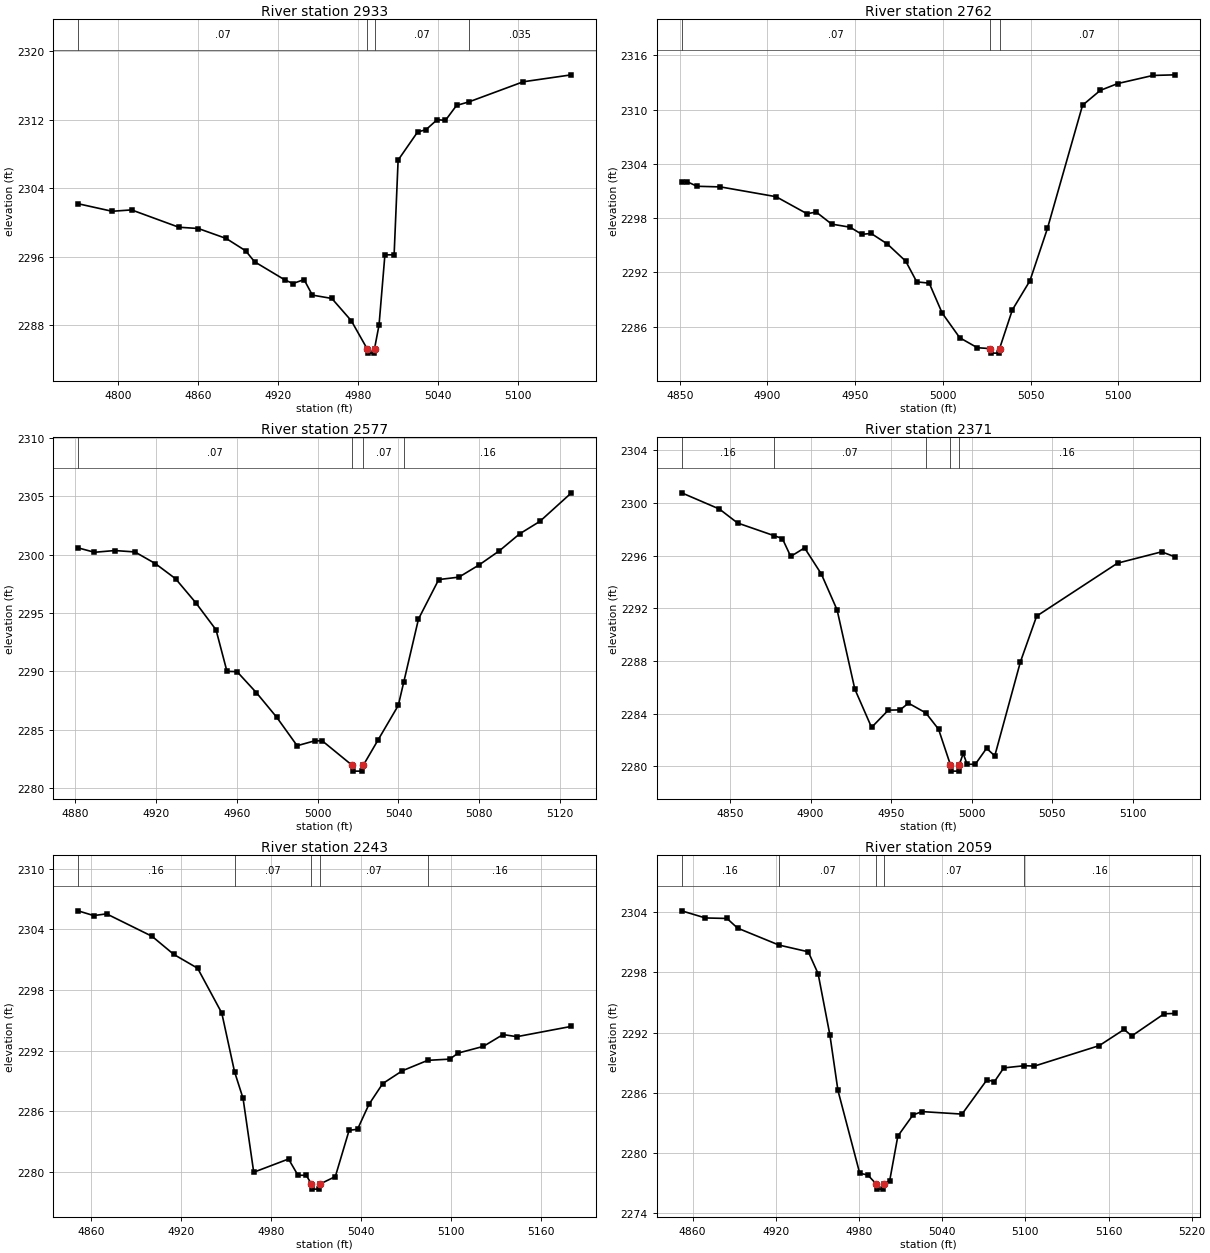
Type RM Length L Ch R = 1,2933,171,171,171
BEGIN DESCRIPTION:
elmc609
END DESCRIPTION:
XS GIS Cut Line= 3
      1499201.07      6767977.75      1499013.36      6767837.79
      1498931.97      6767729.26
#Sta/Elev= 30
  4770.2 2302.20  4795.7 2301.32  4810.3 2301.48  4845.7 2299.46  4860.3 2299.31
  4881.2 2298.15  4895.8 2296.71  4902.5 2295.43  4925.0 2293.33  4931.2 2292.89
  4939.6 2293.35  4945.8 2291.54  4960.4 2291.15  4975.0 2288.55  4986.9 2285.27
  4987.3 2284.77  4991.9 2284.77  4992.4 2285.27  4995.8 2288.05  5000.2 2296.24
  5007.1 2296.24  5010.1 2307.29  5024.7 2310.57  5031.0 2310.84  5039.3 2312.00
  5045.6 2311.93  5053.9 2313.67  5063.3 2314.09  5103.9 2316.43  5140.0 2317.24
#Mann=4,-1,0
  4770.2    0.07       0  4986.9    0.07       0  4992.4    0.07       0
  5063.3   0.035       0
Bank Sta=4986.9,4992.4
Exp/Cntr=0.3,0.1

Type RM Length L Ch R = 1,2762,185,185,185
BEGIN DESCRIPTION:
elmc608
END DESCRIPTION:
XS GIS Cut Line= 3
      1499233.64      6767978.88      1499188.06      6767845.38
      1499181.55      6767705.40
#Sta/Elev= 30
  4851.1 2302.03  4854.2 2302.03  4859.8 2301.52  4873.2 2301.45  4904.9 2300.37
  4922.5 2298.49  4927.8 2298.67  4936.6 2297.34  4947.1 2297.00  4953.8 2296.21
  4959.1 2296.31  4968.3 2295.15  4978.8 2293.25  4985.1 2290.96  4992.2 2290.82
  4999.6 2287.51  5009.6 2284.79  5019.6 2283.69  5026.8 2283.59  5027.3 2283.09
  5031.9 2283.09  5032.3 2283.59  5039.6 2287.87  5049.6 2291.08  5059.6 2296.87
  5079.6 2310.47  5089.7 2312.11  5099.7 2312.87  5119.7 2313.76  5132.3 2313.83
#Mann=3,-1,0
  4851.1    0.07       0  5026.8    0.07       0  5032.3    0.07       0
Bank Sta=5026.8,5032.3
Exp/Cntr=0.3,0.1

Type RM Length L Ch R = 1,2577,206,206,206
BEGIN DESCRIPTION:
elmc607
END DESCRIPTION:
XS GIS Cut Line= 3
      1499366.01      6767956.10      1499372.52      6767835.62
      1499375.76      6767712.42
#Sta/Elev= 30
  4881.6 2300.58  4889.7 2300.20  4899.7 2300.35  4909.7 2300.23  4919.8 2299.23
  4929.8 2297.93  4939.8 2295.87  4949.8 2293.55  4955.2 2289.99  4960.2 2289.96
  4969.8 2288.15  4979.8 2286.05  4989.9 2283.61  4998.6 2284.03  5002.3 2284.03
  5017.1 2281.93  5017.6 2281.43  5022.2 2281.43  5022.6 2281.93  5029.9 2284.10
  5039.9 2287.06  5042.6 2289.06  5049.9 2294.48  5059.9 2297.86  5069.9 2298.07
  5079.9 2299.12  5089.9 2300.33  5099.9 2301.78  5109.9 2302.85  5125.5 2305.30
#Mann=4,-1,0
  4881.6    0.07       0  5017.1    0.07       0  5022.6    0.07       0
  5042.6    0.16       0
Bank Sta=5017.1,5022.6
Exp/Cntr=0.3,0.1

Type RM Length L Ch R = 1,2371,128,128,128
BEGIN DESCRIPTION:
elmc606
END DESCRIPTION:
XS GIS Cut Line= 3
      1499627.52      6768011.43      1499578.68      6767838.87
      1499590.57      6767712.47
#Sta/Elev= 30
  4820.0 2300.76  4843.4 2299.53  4854.7 2298.47  4877.3 2297.51  4882.5 2297.29
  4887.7 2295.93  4896.3 2296.58  4906.7 2294.60  4916.5 2291.87  4927.5 2285.86
  4937.9 2282.95  4948.3 2284.26  4955.6 2284.28  4960.8 2284.79  4971.6 2284.05
  4979.5 2282.81  4986.8 2280.13  4987.2 2279.63  4991.9 2279.63  4992.4 2280.13
  4994.8 2280.97  4997.2 2280.15  5002.3 2280.15  5009.3 2281.36  5014.4 2280.79
  5030.3 2287.92  5040.4 2291.40  5090.6 2295.42  5118.0 2296.28  5126.3 2295.90
#Mann=5,-1,0
  4820.0    0.16       0  4877.3    0.07       0  4971.6    0.16       0
  4986.8    0.07       0  4992.4    0.16       0
Bank Sta=4986.8,4992.4
Exp/Cntr=0.3,0.1

Type RM Length L Ch R = 1,2243,184,184,184
BEGIN DESCRIPTION:
elmc605
END DESCRIPTION:
XS GIS Cut Line= 3
      1499757.73      6767977.79      1499705.64      6767837.79
      1499625.35      6767677.22
#Sta/Elev= 30
  4851.3 2305.84  4861.7 2305.37  4870.3 2305.54  4900.6 2303.32  4915.1 2301.53
  4931.0 2300.16  4947.1 2295.73  4955.6 2289.93  4961.3 2287.28  4968.4 2279.98
  4991.6 2281.29  4997.9 2279.68  5003.4 2279.68  5006.9 2278.81  5007.3 2278.31
  5012.0 2278.31  5012.5 2278.81  5022.8 2279.55  5032.0 2284.13  5037.6 2284.23
  5045.2 2286.69  5054.4 2288.75  5067.5 2290.02  5084.4 2291.05  5099.1 2291.17
  5104.7 2291.77  5121.5 2292.43  5134.6 2293.60  5143.8 2293.39  5180.2 2294.41
#Mann=5,-1,0
  4851.3    0.16       0  4955.6    0.07       0  5006.9    0.07       0
  5012.5    0.07       0  5084.4    0.16       0
Bank Sta=5006.9,5012.5
Exp/Cntr=0.3,0.1

Type RM Length L Ch R = 1,2059,115,115,115
BEGIN DESCRIPTION:
elmc604
END DESCRIPTION:
XS GIS Cut Line= 3
      1499949.75      6767798.71      1499822.82      6767723.86
      1499631.85      6767640.31
#Sta/Elev= 30
  4852.1 2304.13  4869.2 2303.42  4884.8 2303.37  4892.4 2302.41  4922.3 2300.72
  4943.4 2300.05  4950.5 2297.87  4959.0 2291.77  4964.8 2286.25  4980.5 2278.00
  4986.3 2277.83  4992.5 2276.92  4992.9 2276.42  4997.6 2276.42  4998.1 2276.92
  5002.1 2277.24  5008.0 2281.70  5018.9 2283.80  5025.4 2284.14  5054.3 2283.89
  5072.2 2287.29  5077.7 2287.13  5084.4 2288.49  5099.3 2288.71  5106.5 2288.67
  5153.3 2290.71  5171.2 2292.32  5176.7 2291.67  5200.1 2293.88  5207.9 2293.91
#Mann=5,-1,0
  4852.1    0.16       0  4922.3    0.07       0  4992.5    0.07       0
  4998.1    0.07       0  5099.3    0.16       0
Bank Sta=4992.5,4998.1
Exp/Cntr=0.3,0.1

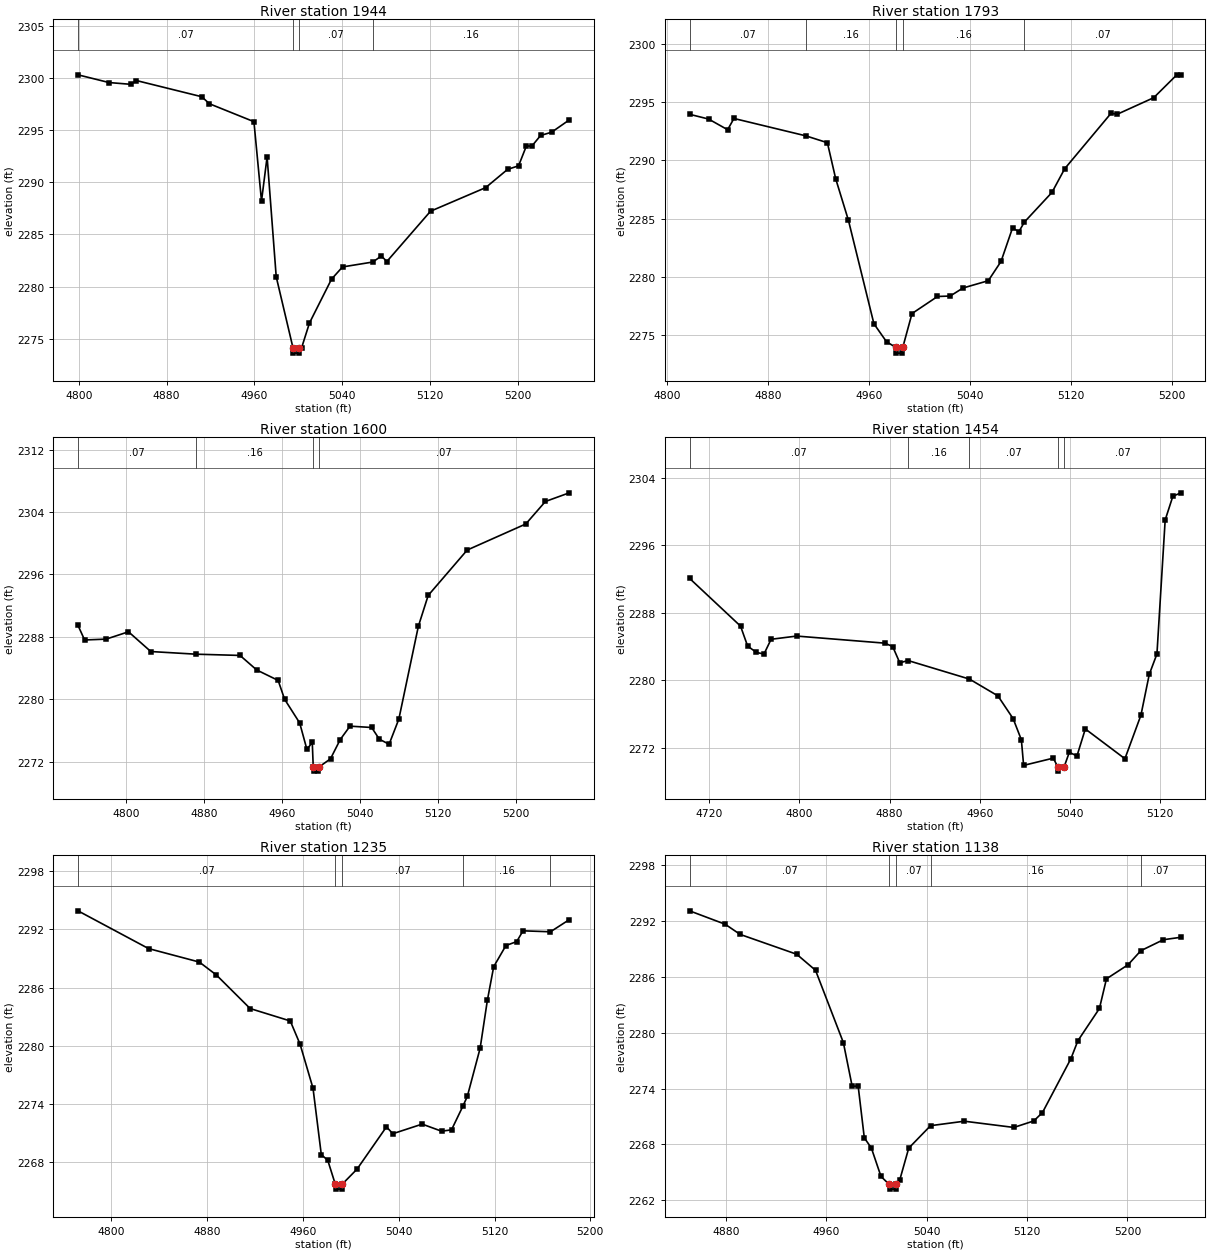
Type RM Length L Ch R = 1,1944,151,151,151
BEGIN DESCRIPTION:
elmc603
END DESCRIPTION:
XS GIS Cut Line= 3
      1500052.87      6767583.88      1499854.29      6767618.60
      1499608.97      6767600.23
#Sta/Elev= 30
  4799.3 2300.30  4827.6 2299.56  4847.5 2299.39  4852.6 2299.75  4912.1 2298.20
  4919.0 2297.53  4959.6 2295.81  4966.5 2288.20  4971.6 2292.44  4979.9 2280.95
  4995.2 2274.13  4995.6 2273.63  5000.3 2273.63  5000.8 2274.13  5003.0 2274.13
  5010.2 2276.52  5030.3 2280.72  5040.3 2281.89  5067.9 2282.36  5075.7 2282.94
  5080.7 2282.41  5120.5 2287.23  5170.7 2289.49  5190.7 2291.24  5200.7 2291.58
  5207.8 2293.48  5212.8 2293.47  5220.8 2294.49  5230.8 2294.80  5246.9 2295.98
#Mann=4,-1,0
  4799.3    0.07       0  4995.2    0.07       0  5000.8    0.07       0
  5067.9    0.16       0
Bank Sta=4995.2,5000.8
Exp/Cntr=0.3,0.1

Type RM Length L Ch R = 1,1793,193,193,193
BEGIN DESCRIPTION:
elmc602
END DESCRIPTION:
XS GIS Cut Line= 3
      1499989.93      6767459.10      1499806.55      6767482.97
      1499603.68      6767455.85
#Sta/Elev= 30
  4817.6 2293.98  4832.7 2293.57  4847.8 2292.65  4852.8 2293.62  4909.9 2292.12
  4926.9 2291.53  4933.5 2288.42  4943.6 2284.84  4963.8 2275.93  4973.8 2274.38
  4981.1 2273.90  4981.6 2273.40  4986.3 2273.40  4986.7 2273.90  4994.0 2276.81
  5014.2 2278.28  5024.3 2278.32  5034.4 2279.01  5054.5 2279.64  5064.6 2281.30
  5073.7 2284.18  5078.8 2283.87  5083.1 2284.69  5105.0 2287.25  5115.1 2289.29
  5151.8 2294.06  5156.9 2293.99  5185.7 2295.41  5204.0 2297.38  5207.2 2297.38
#Mann=5,-1,0
  4817.6    0.07       0  4909.9    0.16       0  4981.1    0.07       0
  4986.7    0.16       0  5083.1    0.07       0
Bank Sta=4981.1,4986.7
Exp/Cntr=0.3,0.1

Type RM Length L Ch R = 1,1600,146,146,146
BEGIN DESCRIPTION:
elmc601
END DESCRIPTION:
XS GIS Cut Line= 3
      1500031.14      6767392.90      1499809.80      6767289.83
      1499550.51      6767305.02
#Sta/Elev= 30
  4750.7 2289.48  4757.5 2287.61  4779.6 2287.72  4802.5 2288.66  4825.4 2286.13
  4871.7 2285.79  4916.9 2285.63  4934.0 2283.77  4956.0 2282.43  4962.6 2280.02
  4978.1 2276.98  4985.5 2273.59  4991.0 2274.49  4992.0 2271.31  4992.4 2270.81
  4997.1 2270.81  4997.6 2271.31  5009.7 2272.39  5019.7 2274.86  5029.7 2276.57
  5051.9 2276.40  5059.8 2274.90  5069.8 2274.25  5079.8 2277.48  5099.8 2289.36
  5109.9 2293.32  5149.9 2299.13  5210.0 2302.47  5230.1 2305.35  5254.6 2306.46
#Mann=4,-1,0
  4750.7    0.07       0  4871.7    0.16       0  4992.0    0.07       0
  4997.6    0.07       0
Bank Sta=4992,4997.6
Exp/Cntr=0.3,0.1

Type RM Length L Ch R = 1,1454,219,219,219
BEGIN DESCRIPTION:
elmc356
END DESCRIPTION:
XS GIS Cut Line= 3
      1500091.92      6767363.61      1499856.77      6767181.69
      1499755.03      6767088.02
#Sta/Elev= 30
  4702.7 2292.08  4747.9 2286.42  4754.2 2284.05  4762.0 2283.30  4768.7 2283.11
  4775.0 2284.86  4797.7 2285.24  4875.8 2284.40  4882.8 2284.00  4889.1 2282.07
  4896.4 2282.34  4950.9 2280.14  4976.1 2278.15  4989.6 2275.45  4996.9 2272.94
  4998.9 2269.91  5025.2 2270.77  5029.2 2269.73  5029.6 2269.23  5034.8 2269.73
  5039.4 2271.46  5046.2 2271.03  5053.6 2274.23  5088.7 2270.70  5102.9 2275.86
  5110.3 2280.70  5117.1 2283.12  5124.4 2299.00  5131.2 2301.81  5138.3 2302.22
#Mann=5,-1,0
  4702.7    0.07       0  4896.4    0.16       0  4950.9    0.07       0
  5029.2    0.07       0  5034.8    0.07       0
Bank Sta=5029.2,5034.8
Exp/Cntr=0.3,0.1

Type RM Length L Ch R = 1,1235,97,97,97
BEGIN DESCRIPTION:
elmc600
END DESCRIPTION:
XS GIS Cut Line= 3
      1500204.74      6767311.50      1500079.98      6767185.66
      1499995.36      6766968.68
#Sta/Elev= 30
  4772.3 2293.91  4831.2 2290.02  4873.6 2288.63  4887.8 2287.30  4916.0 2283.84
  4949.5 2282.56  4957.7 2280.16  4968.5 2275.62  4975.4 2268.79  4980.8 2268.20
  4987.1 2265.73  4987.5 2265.23  4992.3 2265.23  4992.8 2265.73  5005.3 2267.30
  5029.8 2271.65  5035.1 2270.94  5059.6 2271.93  5075.8 2271.20  5084.1 2271.34
  5093.6 2273.78  5097.3 2274.79  5108.0 2279.76  5114.0 2284.67  5119.3 2288.15
  5129.5 2290.33  5138.5 2290.74  5143.8 2291.85  5166.7 2291.75  5182.4 2293.00
#Mann=5,-1,0
  4772.3    0.07       0  4987.1    0.07       0  4992.8    0.07       0
  5093.6    0.16       0  5166.7    0.07       0
Bank Sta=4987.1,4992.8
Exp/Cntr=0.3,0.1

Type RM Length L Ch R = 1,1138,181,181,181
BEGIN DESCRIPTION:
elmc599
END DESCRIPTION:
XS GIS Cut Line= 3
      1500225.38      6767263.78      1500163.53      6767144.43
      1500053.30      6766912.07
#Sta/Elev= 30
  4851.0 2293.08  4879.4 2291.64  4891.3 2290.55  4936.4 2288.42  4951.4 2286.70
  4973.6 2278.94  4980.6 2274.26  4985.4 2274.26  4990.3 2268.71  4995.9 2267.63
  5003.6 2264.57  5010.2 2263.71  5010.7 2263.21  5015.5 2263.21  5015.9 2263.71
  5018.6 2264.22  5025.7 2267.61  5043.1 2270.02  5070.0 2270.50  5109.5 2269.83
  5125.4 2270.53  5132.3 2271.43  5155.0 2277.22  5160.5 2279.13  5177.7 2282.60
  5183.3 2285.78  5200.5 2287.29  5210.7 2288.80  5228.7 2289.98  5242.6 2290.24
#Mann=5,-1,0
  4851.0    0.07       0  5010.2    0.07       0  5015.9    0.07       0
  5043.1    0.16       0  5210.7    0.07       0
Bank Sta=5010.2,5015.9
Exp/Cntr=0.3,0.1

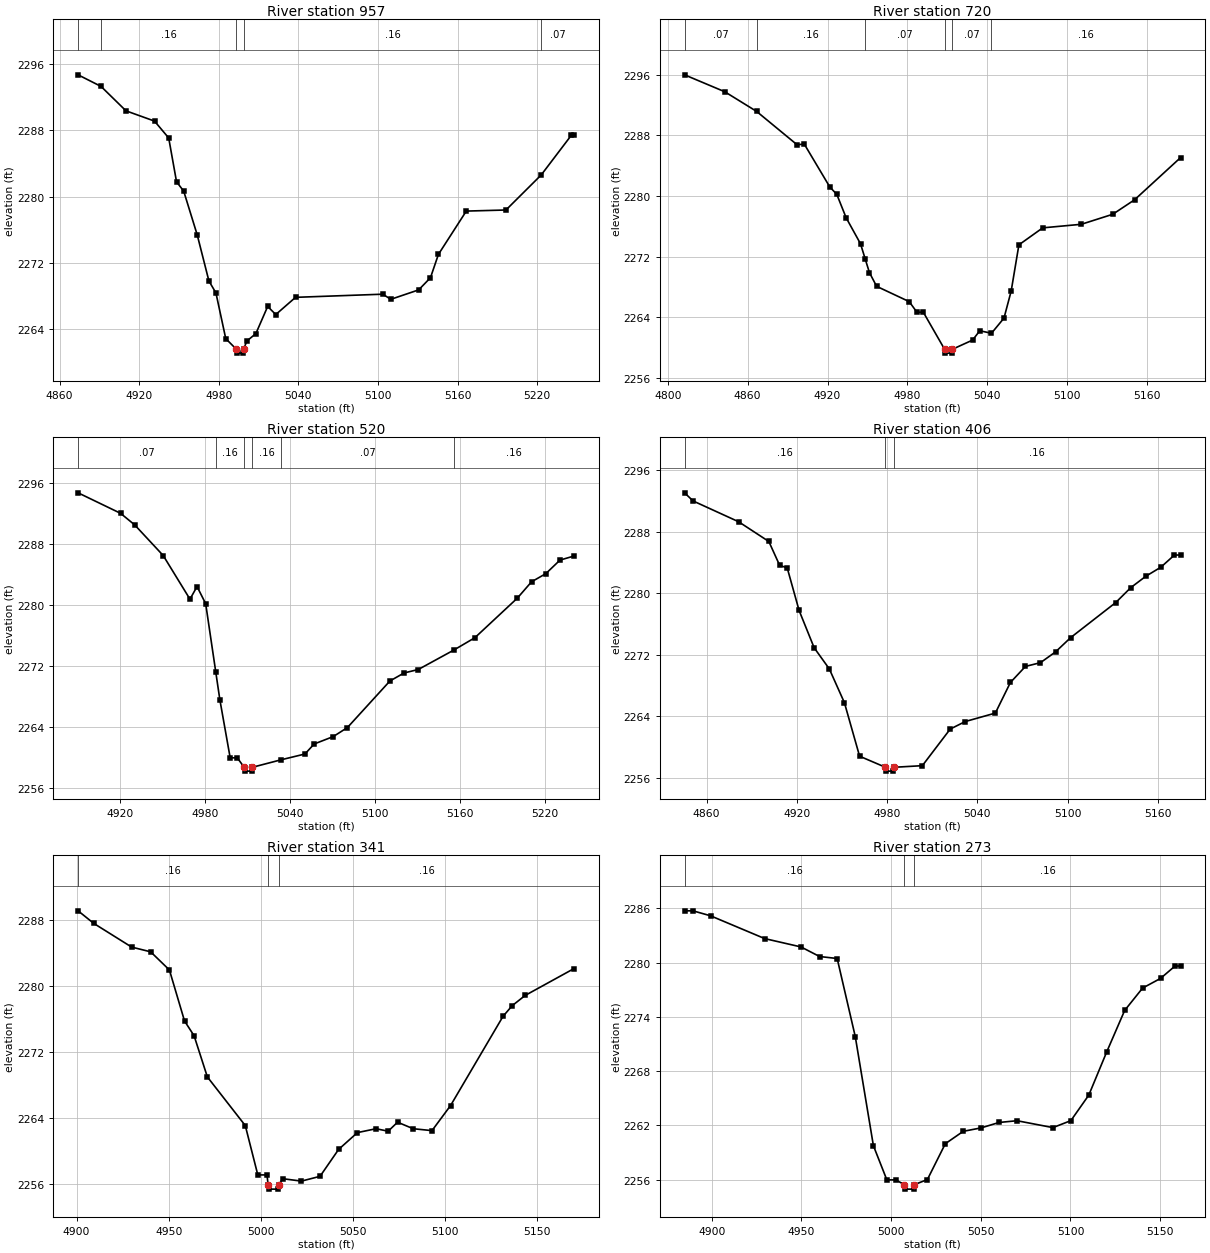
Type RM Length L Ch R = 1,957,237,237,237
BEGIN DESCRIPTION:
elmc598
END DESCRIPTION:
XS GIS Cut Line= 3
      1500418.54      6767080.41      1500300.25      6767033.75
      1500096.29      6766894.89
#Sta/Elev= 30
  4874.0 2294.71  4891.3 2293.31  4910.1 2290.36  4931.6 2289.12  4942.3 2287.08
  4948.2 2281.79  4953.6 2280.66  4963.8 2275.37  4972.6 2269.81  4977.9 2268.36
  4985.3 2262.84  4993.1 2261.59  4993.5 2261.09  4998.3 2261.09  4998.8 2261.59
  5001.2 2262.55  5008.0 2263.45  5016.9 2266.73  5023.0 2265.75  5037.9 2267.83
  5103.7 2268.21  5109.7 2267.59  5130.7 2268.73  5139.6 2270.20  5145.6 2273.02
  5166.6 2278.25  5196.5 2278.38  5223.1 2282.62  5245.7 2287.39  5247.9 2287.39
#Mann=5,-1,0
  4874.0    0.07       0  4891.3    0.16       0  4993.1    0.07       0
  4998.8    0.16       0  5223.1    0.07       0
Bank Sta=4993.1,4998.8
Exp/Cntr=0.3,0.1

Type RM Length L Ch R = 1,720,200,200,200
BEGIN DESCRIPTION:
elmc597
END DESCRIPTION:
XS GIS Cut Line= 3
      1500528.16      6766933.94      1500361.02      6766868.82
      1500183.22      6766792.93
#Sta/Elev= 30
  4812.6 2295.96  4842.8 2293.73  4866.7 2291.14  4897.2 2286.73  4902.5 2286.84
  4921.7 2281.18  4927.0 2280.19  4934.0 2277.11  4944.8 2273.68  4948.3 2271.69
  4951.5 2269.88  4956.9 2268.07  4981.4 2266.05  4987.2 2264.65  4992.0 2264.65
  5008.0 2259.76  5008.4 2259.26  5013.2 2259.26  5013.7 2259.76  5029.0 2260.98
  5034.4 2262.21  5043.2 2261.88  5052.6 2263.88  5058.0 2267.45  5063.8 2273.54
  5081.7 2275.78  5110.7 2276.25  5134.3 2277.57  5150.7 2279.48  5185.3 2285.05
#Mann=6,-1,0
  4812.6    0.07       0  4866.7    0.16       0  4948.3    0.07       0
  5008.0    0.07       0  5013.7    0.07       0  5043.2    0.16       0
Bank Sta=5008,5013.7
Exp/Cntr=0.3,0.1

Type RM Length L Ch R = 1,520,114,114,114
BEGIN DESCRIPTION:
elmc355
END DESCRIPTION:
XS GIS Cut Line= 3
      1500554.97      6766688.00      1500445.57      6766694.61
      1500204.96      6766688.00
#Sta/Elev= 30
  4890.4 2294.66  4920.4 2291.98  4930.4 2290.46  4950.5 2286.46  4969.4 2280.75
  4974.4 2282.40  4980.5 2280.16  4987.6 2271.25  4990.5 2267.61  4997.8 2260.00
  5002.8 2260.00  5007.7 2258.76  5008.2 2258.26  5013.0 2258.26  5013.4 2258.76
  5033.7 2259.74  5050.6 2260.50  5057.1 2261.81  5070.6 2262.78  5080.6 2263.96
  5110.6 2270.05  5120.6 2271.10  5130.6 2271.55  5155.6 2274.08  5170.6 2275.71
  5200.6 2280.89  5210.6 2283.02  5220.7 2284.09  5230.7 2285.86  5240.7 2286.40
#Mann=6,-1,0
  4890.4    0.07       0  4987.6    0.16       0  5007.7    0.07       0
  5013.4    0.16       0  5033.7    0.07       0  5155.6    0.16       0
Bank Sta=5007.7,5013.4
Exp/Cntr=0.3,0.1

Type RM Length L Ch R = 1,406,65,65,65
BEGIN DESCRIPTION:
elmc596
END DESCRIPTION:
XS GIS Cut Line= 3
      1500560.70      6766609.49      1500406.86      6766594.13
      1500231.89      6766597.55
#Sta/Elev= 30
  4845.4 2293.04  4851.1 2291.98  4881.3 2289.28  4901.4 2286.71  4908.6 2283.60
  4913.6 2283.28  4921.5 2277.74  4931.5 2272.89  4941.6 2270.13  4951.6 2265.75
  4961.7 2258.78  4978.9 2257.34  4979.4 2256.84  4984.2 2256.84  4984.6 2257.34
  5003.4 2257.55  5021.9 2262.31  5031.9 2263.29  5051.9 2264.39  5061.9 2268.37
  5071.9 2270.46  5081.9 2270.95  5091.9 2272.35  5101.9 2274.20  5131.9 2278.77
  5141.9 2280.71  5151.9 2282.19  5161.9 2283.37  5170.9 2284.95  5175.0 2284.95
#Mann=3,-1,0
  4845.4    0.16       0  4978.9    0.07       0  4984.6    0.16       0
Bank Sta=4978.9,4984.6
Exp/Cntr=0.3,0.1

Type RM Length L Ch R = 1,341,68,68,68
BEGIN DESCRIPTION:
elmc595
END DESCRIPTION:
XS GIS Cut Line= 3
      1500543.28      6766567.17      1500446.81      6766544.07
      1500278.70      6766517.46
#Sta/Elev= 30
  4900.8 2289.11  4909.3 2287.59  4929.9 2284.72  4940.2 2284.15  4950.4 2281.95
  4958.6 2275.78  4963.8 2273.99  4971.0 2269.01  4991.6 2263.12  4998.4 2257.15
  5003.4 2257.15  5004.0 2255.93  5004.5 2255.43  5009.3 2255.43  5009.7 2255.93
  5012.0 2256.69  5022.1 2256.40  5032.2 2256.98  5042.3 2260.24  5052.5 2262.27
  5062.6 2262.74  5069.2 2262.44  5074.3 2263.53  5082.8 2262.74  5093.0 2262.51
  5103.1 2265.55  5131.6 2276.35  5136.6 2277.64  5143.6 2278.87  5170.2 2282.13
#Mann=3,-1,0
  4900.8    0.16       0  5004.0    0.07       0  5009.7    0.16       0
Bank Sta=5004,5009.7
Exp/Cntr=0.3,0.1

Type RM Length L Ch R = 1,273,64,64,64
BEGIN DESCRIPTION:
elmc594
END DESCRIPTION:
XS GIS Cut Line= 3
      1500569.34      6766492.30      1500455.15      6766477.10
      1500293.77      6766474.94
#Sta/Elev= 30
  4884.8 2285.72  4889.5 2285.72  4899.3 2285.17  4929.5 2282.65  4949.7 2281.73
  4960.1 2280.67  4969.9 2280.45  4980.0 2271.81  4990.1 2259.76  4997.6 2255.98
  5002.6 2255.98  5007.3 2255.46  5007.8 2254.96  5012.6 2254.96  5013.0 2255.46
  5020.2 2256.02  5030.2 2259.98  5040.2 2261.35  5050.2 2261.73  5060.2 2262.33
  5070.2 2262.52  5090.2 2261.76  5100.2 2262.53  5110.2 2265.35  5120.2 2270.13
  5130.2 2274.71  5140.2 2277.18  5150.2 2278.25  5158.3 2279.62  5161.4 2279.62
#Mann=3,-1,0
  4884.8    0.16       0  5007.3    0.07       0  5013.0    0.16       0
Bank Sta=5007.3,5013
Exp/Cntr=0.3,0.1

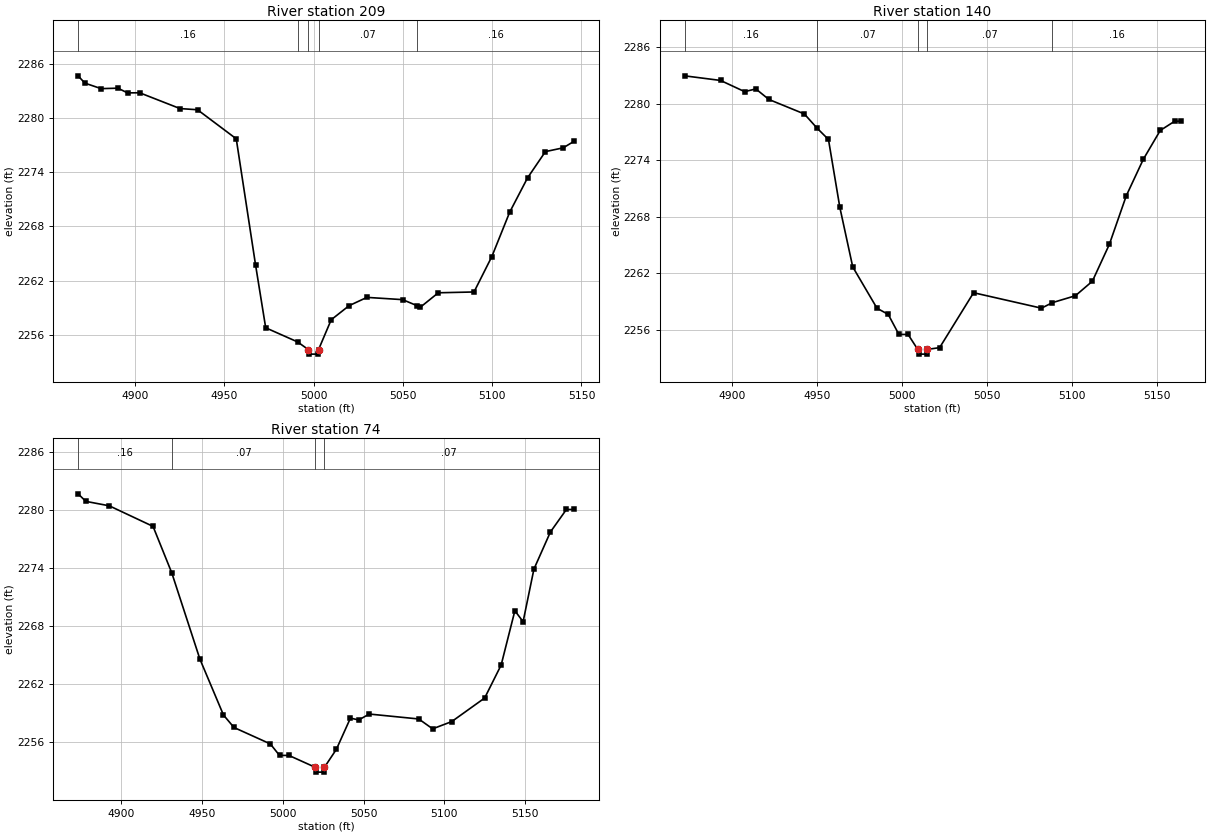
Type RM Length L Ch R = 1,209,69,69,69
BEGIN DESCRIPTION:
elmc593
END DESCRIPTION:
XS GIS Cut Line= 3
      1500576.94      6766463.00      1500454.81      6766412.92
      1500308.93      6766410.94
#Sta/Elev= 30
  4868.0 2284.69  4871.8 2283.88  4880.9 2283.27  4890.3 2283.32  4895.7 2282.80
  4902.5 2282.81  4925.1 2281.06  4934.9 2280.93  4956.6 2277.71  4967.4 2263.75
  4973.1 2256.76  4991.0 2255.19  4997.0 2254.34  4997.5 2253.84  5002.3 2253.84
  5002.7 2254.34  5009.8 2257.65  5019.8 2259.21  5029.8 2260.13  5049.8 2259.88
  5057.9 2259.21  5059.8 2259.05  5069.8 2260.64  5089.8 2260.73  5099.8 2264.66
  5109.8 2269.58  5119.8 2273.38  5129.8 2276.29  5139.8 2276.71  5145.9 2277.44
#Mann=5,-1,0
  4868.0    0.16       0  4991.0    0.07       0  4997.0    0.07       0
  5002.7    0.07       0  5057.9    0.16       0
Bank Sta=4997,5002.7
Exp/Cntr=0.3,0.1

Type RM Length L Ch R = 1,140,66,66,66
BEGIN DESCRIPTION:
elmc592
END DESCRIPTION:
XS GIS Cut Line= 3
      1500584.56      6766438.06      1500487.09      6766354.79
      1500323.00      6766356.67
#Sta/Elev= 30
  4871.8 2282.98  4893.0 2282.49  4907.2 2281.30  4913.8 2281.59  4921.5 2280.47
  4942.4 2278.93  4949.8 2277.44  4956.6 2276.22  4963.3 2269.01  4970.9 2262.69
  4985.2 2258.30  4991.8 2257.65  4998.1 2255.52  5003.5 2255.52  5009.2 2253.93
  5009.7 2253.43  5014.5 2253.43  5014.9 2253.93  5022.1 2254.12  5042.1 2259.95
  5082.1 2258.31  5088.6 2258.90  5102.1 2259.63  5112.1 2261.17  5122.1 2265.08
  5132.1 2270.25  5142.1 2274.11  5152.1 2277.18  5160.6 2278.16  5164.1 2278.16
#Mann=5,-1,0
  4871.8    0.16       0  4949.8    0.07       0  5009.2    0.07       0
  5014.9    0.07       0  5088.6    0.16       0
Bank Sta=5009.2,5014.9
Exp/Cntr=0.3,0.1

Type RM Length L Ch R = 1,74,0,0,0
BEGIN DESCRIPTION:
elmc591
END DESCRIPTION:
XS GIS Cut Line= 3
      1500584.53      6766394.64      1500507.51      6766294.04
      1500330.64      6766329.54
#Sta/Elev= 30
  4873.3 2281.69  4878.1 2280.91  4892.6 2280.45  4919.7 2278.32  4931.3 2273.51
  4948.7 2264.59  4963.3 2258.80  4969.8 2257.51  4992.3 2255.81  4998.0 2254.62
  5003.8 2254.62  5020.1 2253.39  5020.6 2252.89  5025.4 2252.89  5025.8 2253.39
  5033.2 2255.25  5041.9 2258.48  5047.0 2258.29  5053.6 2258.90  5084.2 2258.39
  5092.8 2257.37  5104.6 2258.12  5125.0 2260.56  5135.2 2263.97  5143.7 2269.59
  5148.8 2268.46  5155.5 2273.90  5165.7 2277.74  5175.6 2280.07  5180.4 2280.07
#Mann=4,-1,0
  4873.3    0.16       0  4931.3    0.07       0  5020.1    0.07       0
  5025.8    0.07       0
Bank Sta=5020.1,5025.8
Exp/Cntr=0.3,0.1

Chan Stop Cuts=-1