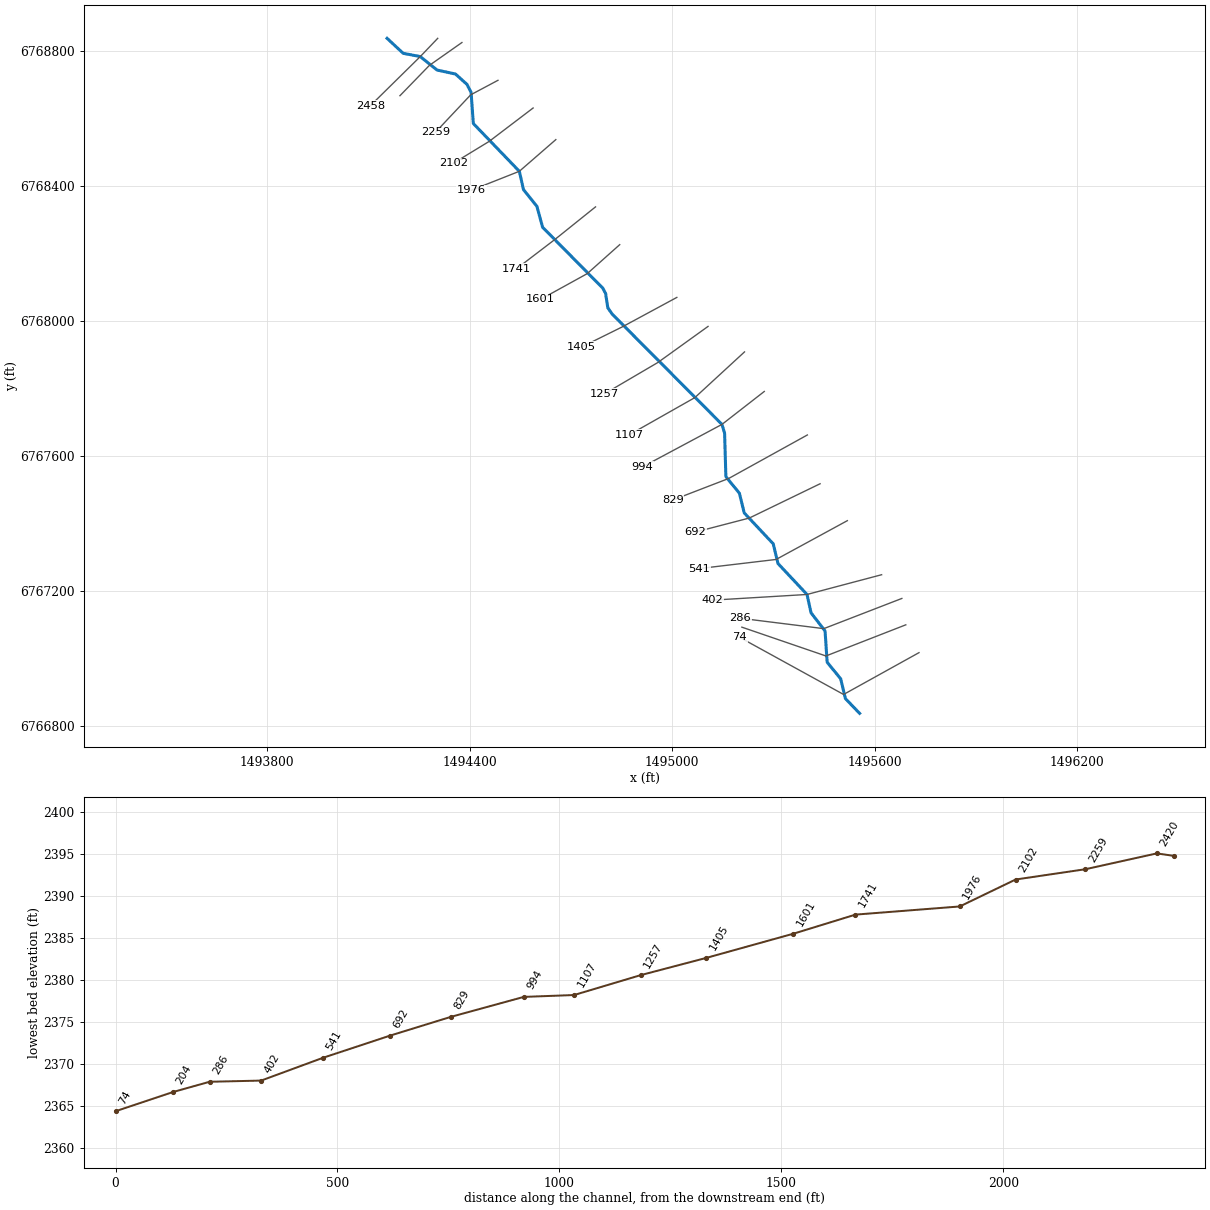
--- Elm 32.prj (project) ---

Proj Title=Elm 32 Base Level Engineering
Current Plan=p01
Default Exp/Contr=0.3,0.1
English Units
Geom File=g01
Flow File=f01
Plan File=p01
BEGIN DESCRIPTION:
Elm 32
END DESCRIPTION:

--- Elm 32.p01 (plan) ---

Plan Title=Multiple Run
Short Identifier=Multiple
Geom File=g01
Flow File=f01
Subcritical Flow
K Sum by GR= 0
Std Step Tol= 0.01
Critical Tol= 0.01
Num of Std Step Trials= 20
Max Error Tol= 0.3
Flow Tol Ratio= 0.001
Split Flow NTrial= 30
Split Flow Tol= 0.02
Split Flow Ratio= 0.02
Log Output Level= 0
Friction Slope Method= 1
Unsteady Friction Slope Method= 2
Unsteady Bridges Friction Slope Method= 1
Parabolic Critical Depth
Global Vel Dist=  1 , 1 , 1
Global Log Level= 0
CheckData=True
Encroach Param= -1, 0, 0, 0
BEGIN DESCRIPTION:
Multiple Run
END DESCRIPTION:

--- Elm 32.f01 (steady flow) ---

Flow Title=Multiple
Number of Profiles=7
Profile Names=10-year,25-year,50-year,1pct_min,100-year,1pct_plu,500-year
River Rch & RM= Elm 32,Reach-1,2458
     164     222     268     202     323     445     473
Boundary for River Rch & Prof#=Elm 32,Reach-1,1
Up Type=0
Dn Type=3
Dn Slope=0.005
Boundary for River Rch & Prof#=Elm 32,Reach-1,2
Up Type=0
Dn Type=3
Dn Slope=0.005
Boundary for River Rch & Prof#=Elm 32,Reach-1,3
Up Type=0
Dn Type=3
Dn Slope=0.005
Boundary for River Rch & Prof#=Elm 32,Reach-1,4
Up Type=0
Dn Type=3
Dn Slope=0.005
Boundary for River Rch & Prof#=Elm 32,Reach-1,5
Up Type=0
Dn Type=3
Dn Slope=0.005
Boundary for River Rch & Prof#=Elm 32,Reach-1,6
Up Type=0
Dn Type=3
Dn Slope=0.005
Boundary for River Rch & Prof#=Elm 32,Reach-1,7
Up Type=0
Dn Type=3
Dn Slope=0.005

--- Elm 32.g01 (geometry) ---

Geom Title=Existing Conditions

River Reach=Elm 32,Reach-1
Reach XY= 30
      1494155.00      6768838.00      1494202.64      6768793.67
      1494253.33      6768783.96      1494302.84      6768744.11
      1494357.58      6768732.29      1494391.74      6768701.66
      1494403.90      6768677.67      1494410.53      6768585.58
      1494546.86      6768444.06      1494559.19      6768389.74
      1494598.90      6768340.19      1494615.76      6768278.32
      1494794.22      6768097.68      1494802.47      6768081.95
      1494808.98      6768039.65      1494821.65      6768021.33
      1495147.18      6767694.19      1495155.02      6767668.01
      1495158.76      6767539.56      1495198.86      6767490.17
      1495213.16      6767431.95      1495299.13      6767340.28
      1495313.18      6767281.96      1495399.16      6767190.29
      1495411.14      6767135.83      1495452.67      6767082.03
      1495458.82      6766989.58      1495498.97      6766940.22
      1495512.91      6766881.85      1495555.00      6766838.00

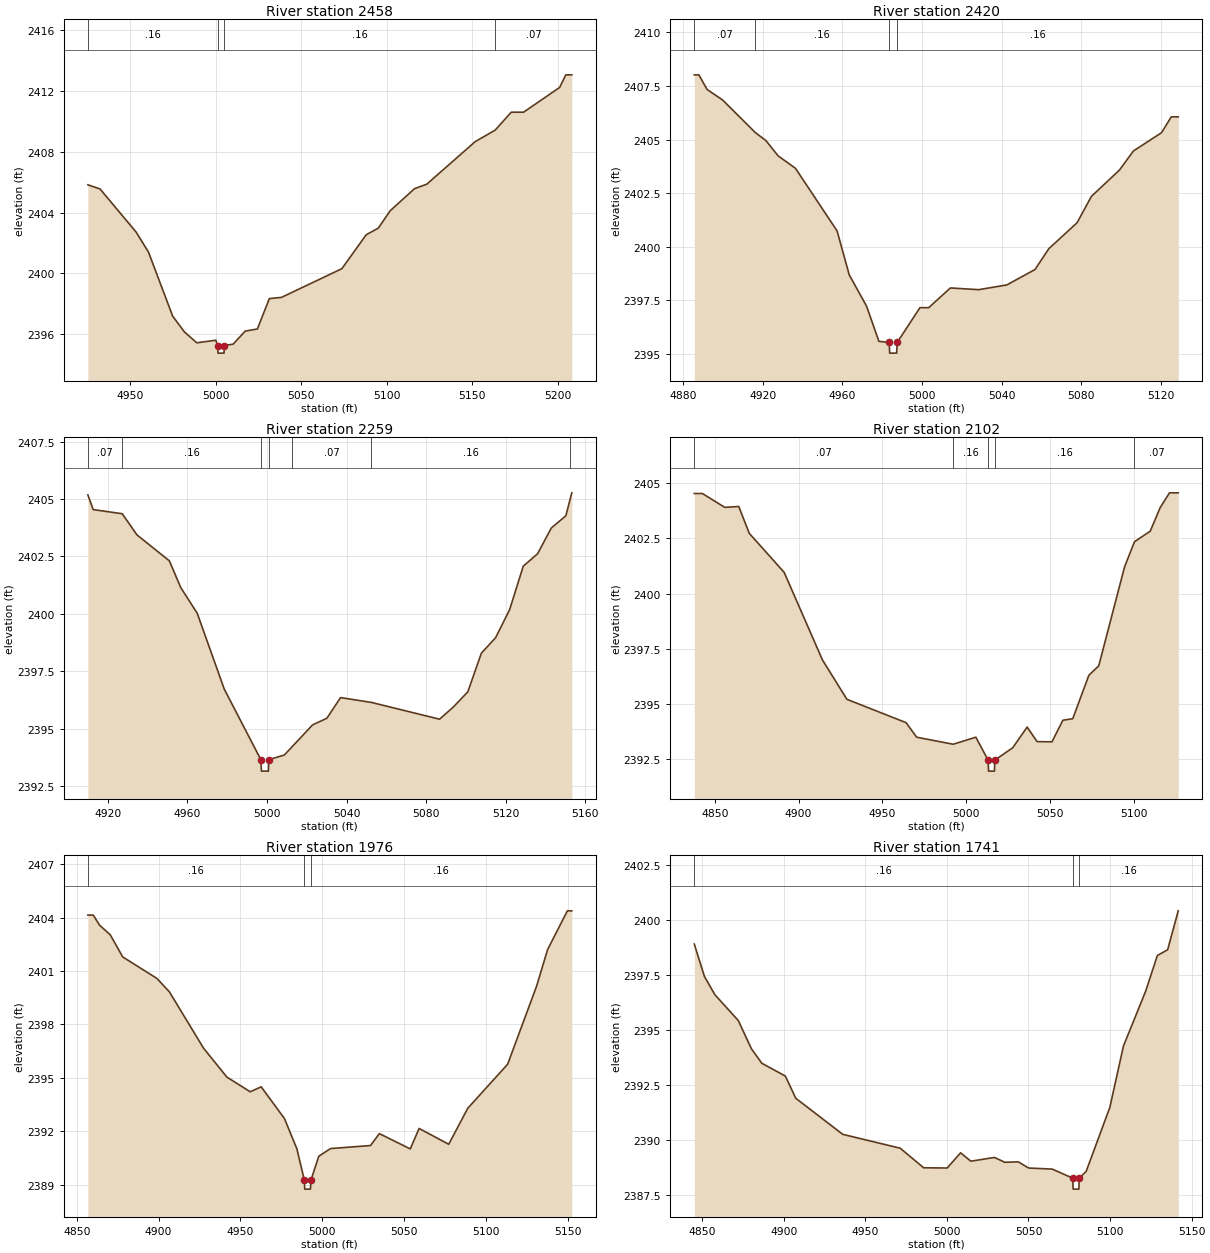
Type RM Length L Ch R = 1,2458,38,38,38
BEGIN DESCRIPTION:
elmc388
END DESCRIPTION:
XS GIS Cut Line= 3
      1494305.02      6768838.02      1494253.33      6768783.96
      1494105.00      6768638.00
#Sta/Elev= 30
  4925.2 2405.83  4932.3 2405.56  4953.4 2402.72  4960.6 2401.41  4974.8 2397.18
  4981.7 2396.14  4988.9 2395.43  5000.0 2395.60  5001.0 2395.25  5001.3 2394.75
  5004.8 2394.75  5005.0 2395.25  5010.1 2395.34  5017.2 2396.20  5024.3 2396.34
  5031.3 2398.34  5038.4 2398.42  5073.7 2400.31  5087.9 2402.54  5095.0 2402.98
  5102.0 2404.13  5116.2 2405.58  5123.3 2405.87  5151.6 2408.67  5163.3 2409.43
  5172.7 2410.61  5179.9 2410.61  5201.0 2412.24  5204.6 2413.07  5208.1 2413.07
#Mann=4,-1,0
  4925.2    0.16       0  5001.0    0.07       0  5005.0    0.16       0
  5163.3    0.07       0
Bank Sta=5001,5005
Exp/Cntr=0.3,0.1

Type RM Length L Ch R = 1,2420,161,161,161
BEGIN DESCRIPTION:
elmc671
END DESCRIPTION:
XS GIS Cut Line= 3
      1494376.73      6768825.62      1494280.40      6768757.93
      1494193.13      6768668.06
#Sta/Elev= 30
  4885.7 2408.02  4888.0 2408.02  4892.1 2407.34  4900.0 2406.84  4916.3 2405.33
  4921.7 2404.95  4927.8 2404.24  4936.5 2403.66  4957.4 2400.74  4963.5 2398.69
  4972.2 2397.23  4978.4 2395.59  4983.6 2395.54  4983.8 2395.04  4987.3 2395.04
  4987.6 2395.54  4999.0 2397.16  5003.4 2397.16  5014.3 2398.08  5028.5 2398.00
  5042.6 2398.22  5056.8 2398.94  5063.7 2399.91  5077.9 2401.12  5085.1 2402.35
  5099.2 2403.58  5106.2 2404.47  5120.3 2405.32  5125.2 2406.06  5128.7 2406.06
#Mann=4,-1,0
  4885.7    0.07       0  4916.3    0.16       0  4983.6    0.07       0
  4987.6    0.16       0
Bank Sta=4983.6,4987.6
Exp/Cntr=0.3,0.1

Type RM Length L Ch R = 1,2259,157,157,157
BEGIN DESCRIPTION:
elmc670
END DESCRIPTION:
XS GIS Cut Line= 3
      1494483.54      6768713.67      1494402.79      6768670.69
      1494298.63      6768560.10
#Sta/Elev= 30
  4909.9 2405.18  4912.6 2404.54  4927.2 2404.36  4934.6 2403.44  4950.9 2402.31
  4956.6 2401.15  4964.9 2400.03  4978.5 2396.73  4996.9 2393.66  4997.2 2393.16
  5000.7 2393.16  5000.9 2393.66  5008.7 2393.86  5012.4 2394.20  5022.9 2395.17
  5030.1 2395.46  5037.0 2396.36  5052.5 2396.15  5086.8 2395.42  5093.7 2395.95
  5101.0 2396.61  5107.8 2398.29  5115.0 2398.97  5122.0 2400.18  5128.9 2402.08
  5136.1 2402.62  5143.0 2403.74  5150.3 2404.27  5152.6 2405.04  5153.3 2405.27
#Mann=7,-1,0
  4909.9    0.07       0  4927.2    0.16       0  4996.9    0.07       0
  5000.9    0.16       0  5012.4    0.07       0  5052.5    0.16       0
  5152.6    0.07       0
Bank Sta=4996.9,5000.9
Exp/Cntr=0.3,0.1

Type RM Length L Ch R = 1,2102,126,126,126
BEGIN DESCRIPTION:
elmc669
END DESCRIPTION:
XS GIS Cut Line= 3
      1494587.69      6768631.63      1494457.48      6768532.67
      1494350.71      6768467.57
#Sta/Elev= 30
  4837.8 2404.54  4842.6 2404.54  4856.0 2403.91  4864.3 2403.95  4870.6 2402.73
  4891.4 2400.96  4914.2 2396.99  4928.8 2395.20  4964.1 2394.14  4970.4 2393.48
  4992.2 2393.16  5005.7 2393.48  5013.0 2392.44  5013.3 2391.94  5016.8 2391.94
  5017.0 2392.44  5027.7 2393.00  5036.3 2393.94  5042.2 2393.28  5051.1 2393.27
  5057.6 2394.25  5063.5 2394.32  5073.1 2396.29  5079.0 2396.72  5094.4 2401.21
  5100.3 2402.35  5109.7 2402.83  5115.7 2403.91  5121.2 2404.57  5126.4 2404.57
#Mann=5,-1,0
  4837.8    0.07       0  4992.2    0.16       0  5013.0    0.07       0
  5017.0    0.16       0  5100.3    0.07       0
Bank Sta=5013,5017
Exp/Cntr=0.3,0.1

Type RM Length L Ch R = 1,1976,235,235,235
BEGIN DESCRIPTION:
elmc387
END DESCRIPTION:
XS GIS Cut Line= 3
      1494654.96      6768537.97      1494546.86      6768444.06
      1494405.03      6768388.01
#Sta/Elev= 30
  4856.8 2404.14  4860.1 2404.14  4863.9 2403.58  4870.5 2403.03  4878.1 2401.79
  4899.0 2400.58  4906.6 2399.83  4927.5 2396.66  4941.7 2395.04  4956.0 2394.21
  4962.7 2394.49  4976.9 2392.71  4984.5 2391.01  4989.1 2389.24  4989.3 2388.74
  4992.8 2388.74  4993.1 2389.24  4997.9 2390.59  5005.1 2391.02  5029.5 2391.19
  5034.9 2391.86  5053.8 2391.00  5059.2 2392.15  5077.3 2391.26  5088.9 2393.28
  5113.3 2395.76  5131.0 2400.15  5137.7 2402.20  5149.8 2404.38  5152.5 2404.38
#Mann=3,-1,0
  4856.8    0.16       0  4989.1    0.07       0  4993.1    0.16       0
Bank Sta=4989.1,4993.1
Exp/Cntr=0.3,0.1

Type RM Length L Ch R = 1,1741,140,140,140
BEGIN DESCRIPTION:
elmc668
END DESCRIPTION:
XS GIS Cut Line= 3
      1494772.58      6768338.66      1494654.09      6768243.60
      1494539.12      6768155.76
#Sta/Elev= 30
  4845.2 2398.91  4851.4 2397.44  4857.8 2396.61  4872.2 2395.43  4880.2 2394.15
  4886.6 2393.49  4901.0 2392.91  4907.4 2391.90  4936.2 2390.26  4971.4 2389.63
  4985.8 2388.74  5000.2 2388.73  5008.4 2389.42  5014.7 2389.04  5029.2 2389.21
  5035.5 2388.99  5043.8 2389.01  5050.1 2388.73  5064.6 2388.68  5077.1 2388.27
  5077.4 2387.77  5080.9 2387.77  5081.1 2388.27  5085.4 2388.58  5099.9 2391.49
  5108.2 2394.27  5121.8 2396.76  5129.0 2398.39  5135.3 2398.65  5141.8 2400.42
#Mann=3,-1,0
  4845.2    0.16       0  5077.1    0.07       0  5081.1    0.16       0
Bank Sta=5077.1,5081.1
Exp/Cntr=0.3,0.1

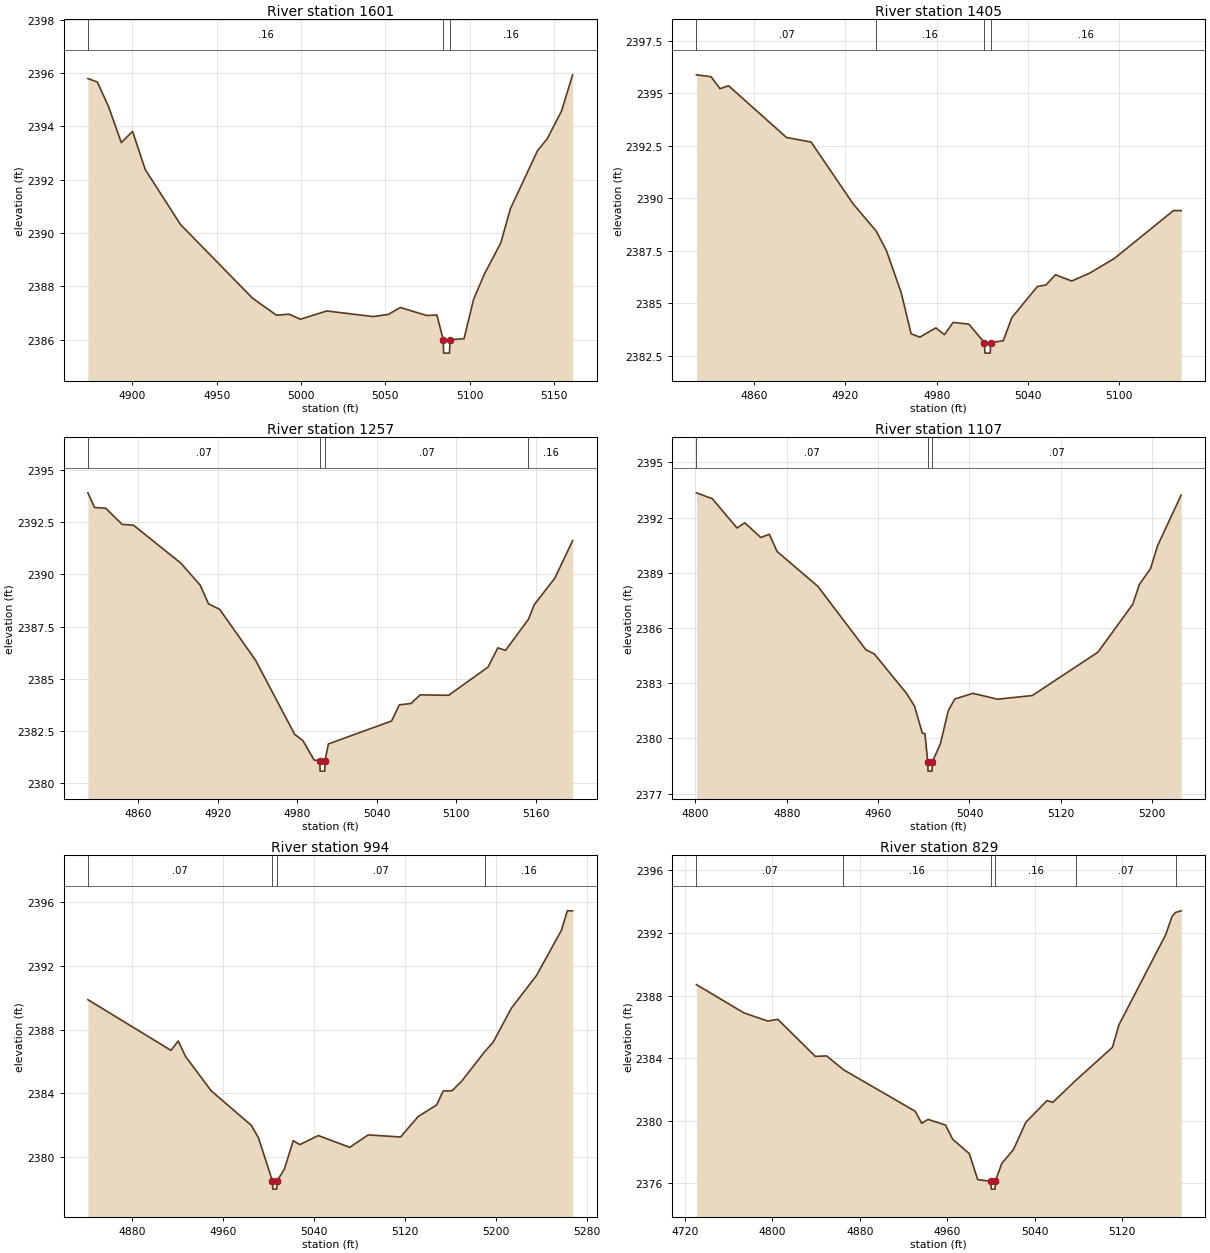
Type RM Length L Ch R = 1,1601,196,196,196
BEGIN DESCRIPTION:
elmc667
END DESCRIPTION:
XS GIS Cut Line= 3
      1494844.21      6768226.69      1494747.84      6768140.74
      1494609.25      6768064.32
#Sta/Elev= 30
  4873.6 2395.79  4879.2 2395.66  4885.9 2394.73  4893.4 2393.39  4900.1 2393.81
  4907.6 2392.38  4928.5 2390.32  4971.2 2387.56  4985.4 2386.92  4992.9 2386.96
  4999.6 2386.77  5015.2 2387.08  5042.7 2386.87  5051.7 2386.95  5058.8 2387.21
  5074.5 2386.91  5080.5 2386.93  5084.3 2386.00  5084.5 2385.50  5088.0 2385.50
  5088.3 2386.00  5096.6 2386.04  5102.3 2387.52  5108.8 2388.48  5118.4 2389.63
  5124.1 2390.91  5140.2 2393.09  5145.9 2393.53  5154.4 2394.57  5161.0 2395.93
#Mann=3,-1,0
  4873.6    0.16       0  5084.3    0.07       0  5088.3    0.16       0
Bank Sta=5084.3,5088.3
Exp/Cntr=0.3,0.1

Type RM Length L Ch R = 1,1405,148,148,148
BEGIN DESCRIPTION:
elmc666
END DESCRIPTION:
XS GIS Cut Line= 3
      1495013.46      6768070.42      1494852.01      6767983.19
      1494730.93      6767923.30
#Sta/Elev= 30
  4822.1 2395.87  4831.7 2395.78  4837.6 2395.21  4843.2 2395.35  4881.3 2392.89
  4897.5 2392.67  4925.1 2389.73  4940.3 2388.43  4947.0 2387.50  4956.7 2385.50
  4963.2 2383.55  4968.9 2383.39  4979.4 2383.83  4985.1 2383.51  4990.8 2384.09
  5001.1 2384.01  5011.4 2383.13  5011.7 2382.63  5015.2 2382.63  5015.4 2383.13
  5023.8 2383.22  5029.4 2384.32  5046.2 2385.80  5051.8 2385.87  5058.1 2386.36
  5068.7 2386.06  5080.4 2386.43  5096.7 2387.13  5135.6 2389.41  5140.7 2389.41
#Mann=4,-1,0
  4822.1    0.07       0  4940.3    0.16       0  5011.4    0.07       0
  5015.4    0.16       0
Bank Sta=5011.4,5015.4
Exp/Cntr=0.3,0.1

Type RM Length L Ch R = 1,1257,150,150,150
BEGIN DESCRIPTION:
elmc665
END DESCRIPTION:
XS GIS Cut Line= 3
      1495105.94      6767984.51      1494957.48      6767877.72
      1494799.97      6767785.30
#Sta/Elev= 30
  4822.2 2393.90  4827.2 2393.20  4835.7 2393.16  4848.0 2392.39  4856.6 2392.35
  4892.2 2390.54  4906.9 2389.48  4913.1 2388.59  4921.6 2388.32  4948.7 2385.88
  4978.1 2382.34  4984.3 2382.04  4992.8 2381.11  4997.0 2381.08  4997.3 2380.58
  5000.8 2380.58  5001.0 2381.08  5003.5 2381.88  5051.2 2382.98  5057.0 2383.75
  5065.9 2383.82  5072.7 2384.23  5094.2 2384.21  5123.9 2385.56  5131.3 2386.48
  5137.1 2386.36  5154.4 2387.85  5158.7 2388.54  5174.3 2389.82  5187.7 2391.61
#Mann=4,-1,0
  4822.2    0.07       0  4997.0    0.07       0  5001.0    0.07       0
  5154.4    0.16       0
Bank Sta=4997,5001
Exp/Cntr=0.3,0.1

Type RM Length L Ch R = 1,1107,113,113,113
BEGIN DESCRIPTION:
elmc664
END DESCRIPTION:
XS GIS Cut Line= 3
      1495213.99      6767908.97      1495066.85      6767773.55
      1494871.68      6767662.95
#Sta/Elev= 30
  4801.0 2393.35  4814.9 2393.03  4836.5 2391.44  4843.3 2391.72  4857.4 2390.92
  4864.8 2391.10  4871.6 2390.16  4907.4 2388.26  4949.3 2384.82  4956.7 2384.59
  4985.1 2382.43  4991.9 2381.75  4998.8 2380.27  5001.0 2380.27  5003.5 2378.72
  5003.7 2378.22  5007.2 2378.22  5007.5 2378.72  5014.6 2379.72  5021.4 2381.50
  5027.1 2382.14  5043.0 2382.45  5064.6 2382.13  5095.0 2382.33  5152.5 2384.69
  5182.9 2387.29  5188.7 2388.37  5198.5 2389.23  5204.6 2390.47  5225.3 2393.23
#Mann=3,-1,0
  4801.0    0.07       0  5003.5    0.07       0  5007.5    0.07       0
Bank Sta=5003.5,5007.5
Exp/Cntr=0.3,0.1

Type RM Length L Ch R = 1,994,165,165,165
BEGIN DESCRIPTION:
elmc386
END DESCRIPTION:
XS GIS Cut Line= 3
      1495272.58      6767791.78      1495147.18      6767694.19
      1494911.63      6767568.27
#Sta/Elev= 30
  4841.1 2389.88  4914.1 2386.70  4920.5 2387.29  4926.8 2386.33  4949.4 2384.17
  4984.7 2382.00  4991.0 2381.22  5003.3 2378.50  5003.6 2378.00  5007.1 2378.00
  5007.3 2378.50  5013.8 2379.27  5021.6 2381.04  5027.3 2380.79  5043.6 2381.36
  5071.2 2380.62  5087.4 2381.40  5115.9 2381.27  5131.3 2382.55  5147.6 2383.28
  5153.3 2384.15  5161.2 2384.17  5169.6 2384.77  5189.8 2386.62  5197.2 2387.21
  5213.4 2389.36  5235.4 2391.40  5257.3 2394.24  5262.4 2395.45  5267.1 2395.45
#Mann=4,-1,0
  4841.1    0.07       0  5003.3    0.07       0  5007.3    0.07       0
  5189.8    0.16       0
Bank Sta=5003.3,5007.3
Exp/Cntr=0.3,0.1

Type RM Length L Ch R = 1,829,137,137,137
BEGIN DESCRIPTION:
elmc663
END DESCRIPTION:
XS GIS Cut Line= 3
      1495400.22      6767662.89      1495167.12      6767533.97
      1495001.78      6767470.18
#Sta/Elev= 30
  4730.5 2388.70  4774.0 2386.89  4795.8 2386.37  4805.0 2386.48  4839.3 2384.11
  4849.6 2384.14  4865.0 2383.26  4930.7 2380.60  4936.7 2379.83  4942.4 2380.08
  4958.4 2379.72  4965.0 2378.81  4980.2 2377.89  4987.9 2376.23  5000.0 2376.12
  5000.3 2375.62  5003.8 2375.62  5004.0 2376.12  5009.9 2377.26  5020.6 2378.15
  5032.0 2379.90  5051.3 2381.28  5056.6 2381.17  5077.7 2382.58  5111.2 2384.69
  5117.1 2386.12  5159.9 2391.89  5165.8 2393.07  5169.0 2393.32  5174.1 2393.42
#Mann=6,-1,0
  4730.5    0.07       0  4865.0    0.16       0  5000.0    0.07       0
  5004.0    0.16       0  5077.7    0.07       0  5169.0    0.16       0
Bank Sta=5000,5004
Exp/Cntr=0.3,0.1

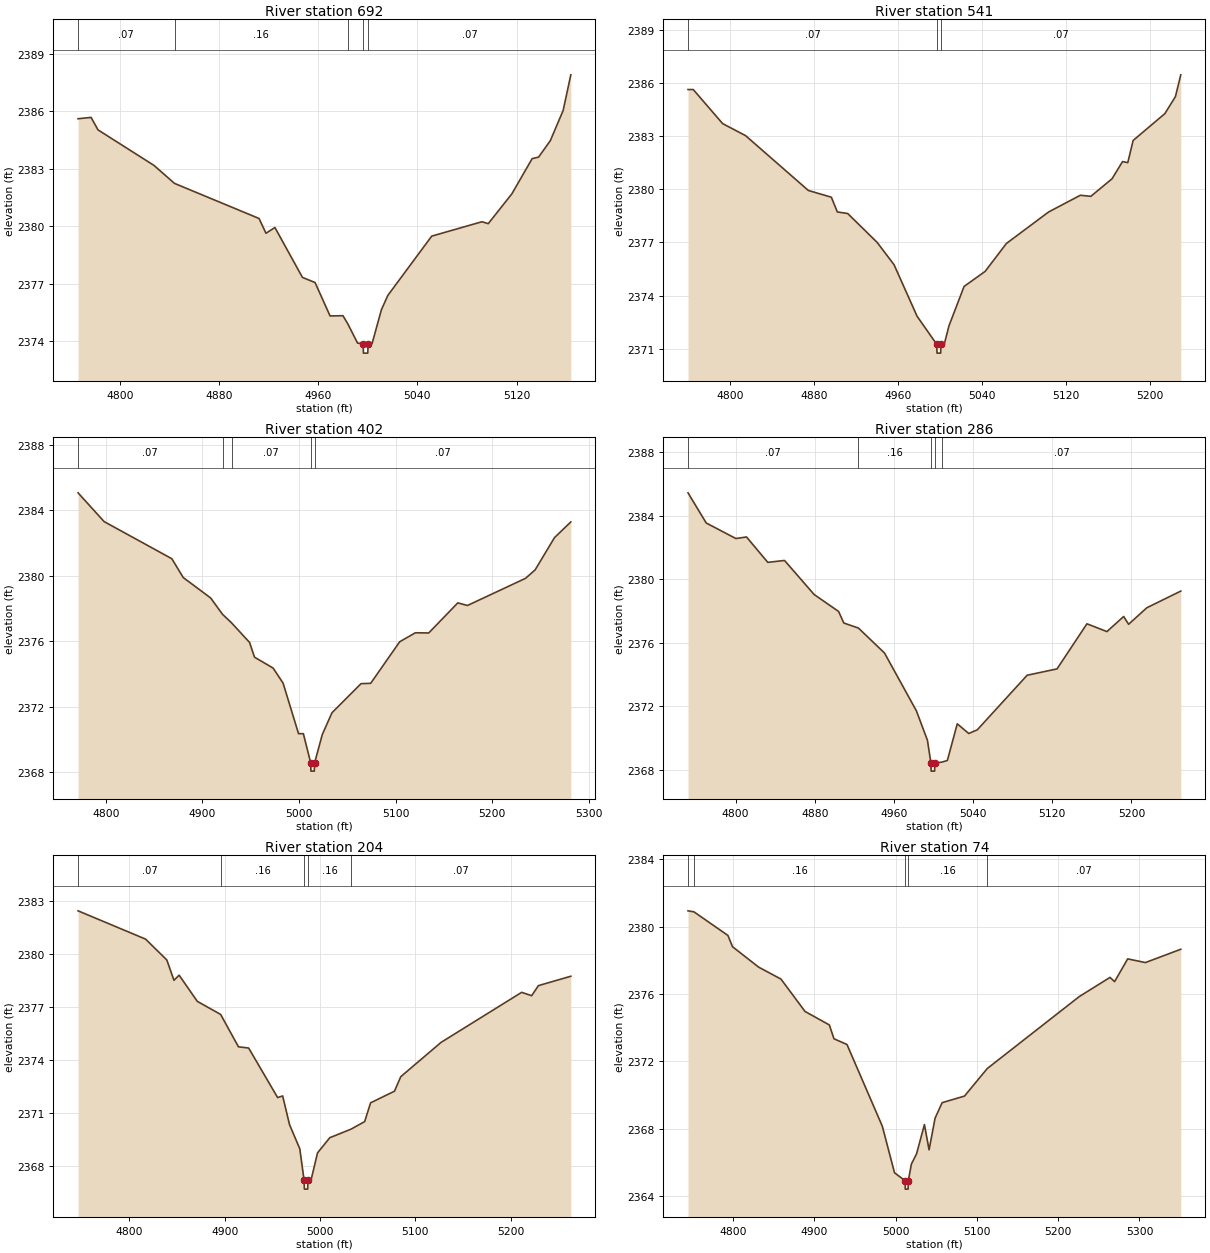
Type RM Length L Ch R = 1,692,151,151,151
BEGIN DESCRIPTION:
elmc662
END DESCRIPTION:
XS GIS Cut Line= 3
      1495437.94      6767518.34      1495228.31      6767416.78
      1495069.04      6767375.35
#Sta/Elev= 30
  4766.3 2385.61  4776.8 2385.68  4782.4 2385.03  4827.5 2383.18  4844.1 2382.24
  4912.3 2380.41  4917.9 2379.64  4925.1 2379.94  4947.3 2377.34  4957.5 2377.07
  4969.6 2375.33  4980.0 2375.34  4983.8 2374.93  4991.8 2373.91  4996.3 2373.89
  4996.5 2373.39  5000.0 2373.39  5000.3 2373.89  5003.5 2373.89  5011.0 2375.65
  5016.2 2376.40  5051.6 2379.49  5092.1 2380.24  5097.2 2380.14  5116.3 2381.70
  5132.6 2383.53  5137.8 2383.61  5147.3 2384.47  5157.6 2386.04  5163.8 2387.90
#Mann=5,-1,0
  4766.3    0.07       0  4844.1    0.16       0  4983.8    0.07       0
  4996.3    0.07       0  5000.3    0.07       0
Bank Sta=4996.3,5000.3
Exp/Cntr=0.3,0.1

Type RM Length L Ch R = 1,541,139,139,139
BEGIN DESCRIPTION:
elmc385
END DESCRIPTION:
XS GIS Cut Line= 3
      1495518.69      6767408.98      1495307.54      6767294.05
      1495079.94      6767267.05
#Sta/Elev= 30
  4759.6 2385.62  4764.6 2385.62  4792.6 2383.70  4814.5 2383.02  4874.3 2379.93
  4896.2 2379.55  4901.9 2378.72  4911.8 2378.63  4939.9 2377.00  4956.0 2375.74
  4977.9 2372.84  4996.6 2371.26  4996.9 2370.76  5000.4 2370.76  5000.6 2371.26
  5003.8 2371.26  5008.3 2372.30  5022.7 2374.52  5042.8 2375.37  5063.0 2376.94
  5103.3 2378.72  5133.5 2379.66  5143.5 2379.60  5163.7 2380.59  5173.7 2381.56
  5178.7 2381.50  5183.8 2382.75  5214.0 2384.26  5224.1 2385.22  5229.2 2386.45
#Mann=3,-1,0
  4759.6    0.07       0  4996.6    0.07       0  5000.6    0.07       0
Bank Sta=4996.6,5000.6
Exp/Cntr=0.3,0.1

Type RM Length L Ch R = 1,402,116,116,116
BEGIN DESCRIPTION:
elmc661
END DESCRIPTION:
XS GIS Cut Line= 3
      1495620.24      6767248.81      1495399.16      6767190.29
      1495118.16      6767173.40
#Sta/Elev= 30
  4771.3 2385.08  4798.3 2383.32  4868.4 2381.05  4880.2 2379.90  4908.6 2378.65
  4920.9 2377.65  4930.2 2377.13  4948.9 2375.93  4954.0 2375.03  4973.3 2374.36
  4983.6 2373.44  4999.6 2370.35  5004.6 2370.35  5012.2 2368.56  5012.4 2368.06
  5015.9 2368.06  5016.2 2368.56  5024.2 2370.30  5034.2 2371.63  5064.3 2373.41
  5074.3 2373.43  5104.3 2375.97  5120.5 2376.52  5134.4 2376.51  5164.5 2378.35
  5174.5 2378.19  5234.6 2379.85  5244.6 2380.37  5264.6 2382.34  5281.5 2383.30
#Mann=5,-1,0
  4771.3    0.07       0  4920.9    0.16       0  4930.2    0.07       0
  5012.2    0.07       0  5016.2    0.07       0
Bank Sta=5012.2,5016.2
Exp/Cntr=0.3,0.1

Type RM Length L Ch R = 1,286,82,82,82
BEGIN DESCRIPTION:
elmc660
END DESCRIPTION:
XS GIS Cut Line= 3
      1495680.15      6767178.51      1495448.85      6767089.05
      1495200.96      6767119.91
#Sta/Elev= 30
  4752.0 2385.45  4770.4 2383.55  4800.4 2382.57  4811.1 2382.67  4832.6 2381.07
  4849.5 2381.19  4879.5 2379.04  4904.1 2377.98  4909.4 2377.25  4924.2 2376.93
  4950.5 2375.36  4982.7 2371.72  4993.9 2369.86  4997.4 2368.42  4997.6 2367.92
  5001.1 2367.92  5001.4 2368.42  5008.6 2368.49  5014.0 2368.59  5024.0 2370.90
  5035.6 2370.29  5044.2 2370.52  5094.6 2373.96  5124.8 2374.36  5155.0 2377.20
  5175.2 2376.71  5192.1 2377.66  5197.1 2377.17  5215.5 2378.21  5249.8 2379.26
#Mann=5,-1,0
  4752.0    0.07       0  4924.2    0.16       0  4997.4    0.07       0
  5001.4    0.16       0  5008.6    0.07       0
Bank Sta=4997.4,5001.4
Exp/Cntr=0.3,0.1

Type RM Length L Ch R = 1,204,130,130,130
BEGIN DESCRIPTION:
elmc659
END DESCRIPTION:
XS GIS Cut Line= 3
      1495691.87      6767100.38      1495455.23      6767008.09
      1495206.14      6767093.43
#Sta/Elev= 30
  4746.0 2382.45  4816.9 2380.85  4839.2 2379.67  4846.7 2378.52  4852.1 2378.81
  4871.2 2377.33  4895.7 2376.59  4914.4 2374.76  4925.1 2374.69  4955.5 2371.89
  4960.8 2371.98  4968.0 2370.36  4978.8 2368.99  4983.3 2367.21  4983.6 2366.71
  4987.1 2366.71  4987.3 2367.21  4990.7 2367.25  4997.4 2368.76  5010.3 2369.62
  5032.5 2370.10  5046.9 2370.53  5053.1 2371.59  5078.2 2372.25  5084.8 2373.07
  5127.1 2375.01  5211.7 2377.84  5222.2 2377.65  5229.3 2378.22  5263.3 2378.75
#Mann=5,-1,0
  4746.0    0.07       0  4895.7    0.16       0  4983.3    0.07       0
  4987.3    0.16       0  5032.5    0.07       0
Bank Sta=4983.3,4987.3
Exp/Cntr=0.3,0.1

Type RM Length L Ch R = 1,74,0,0,0
BEGIN DESCRIPTION:
elmc658
END DESCRIPTION:
XS GIS Cut Line= 3
      1495730.96      6767017.93      1495507.51      6766894.04
      1495200.09      6767063.01
#Sta/Elev= 30
  4744.5 2380.93  4751.8 2380.87  4793.6 2379.47  4799.3 2378.80  4831.4 2377.59
  4858.9 2376.88  4888.5 2374.96  4918.4 2374.16  4924.1 2373.34  4940.1 2373.00
  4983.6 2368.15  4998.6 2365.39  5011.6 2364.92  5011.8 2364.42  5015.3 2364.42
  5015.6 2364.92  5019.3 2365.90  5025.7 2366.51  5035.4 2368.25  5041.1 2366.75
  5048.5 2368.63  5057.2 2369.55  5084.7 2369.94  5112.6 2371.57  5225.8 2375.84
  5263.7 2376.98  5269.4 2376.73  5285.5 2378.08  5307.3 2377.86  5350.8 2378.65
#Mann=5,-1,0
  4744.5    0.07       0  4751.8    0.16       0  5011.6    0.07       0
  5015.6    0.16       0  5112.6    0.07       0
Bank Sta=5011.6,5015.6
Exp/Cntr=0.3,0.1

Chan Stop Cuts=-1