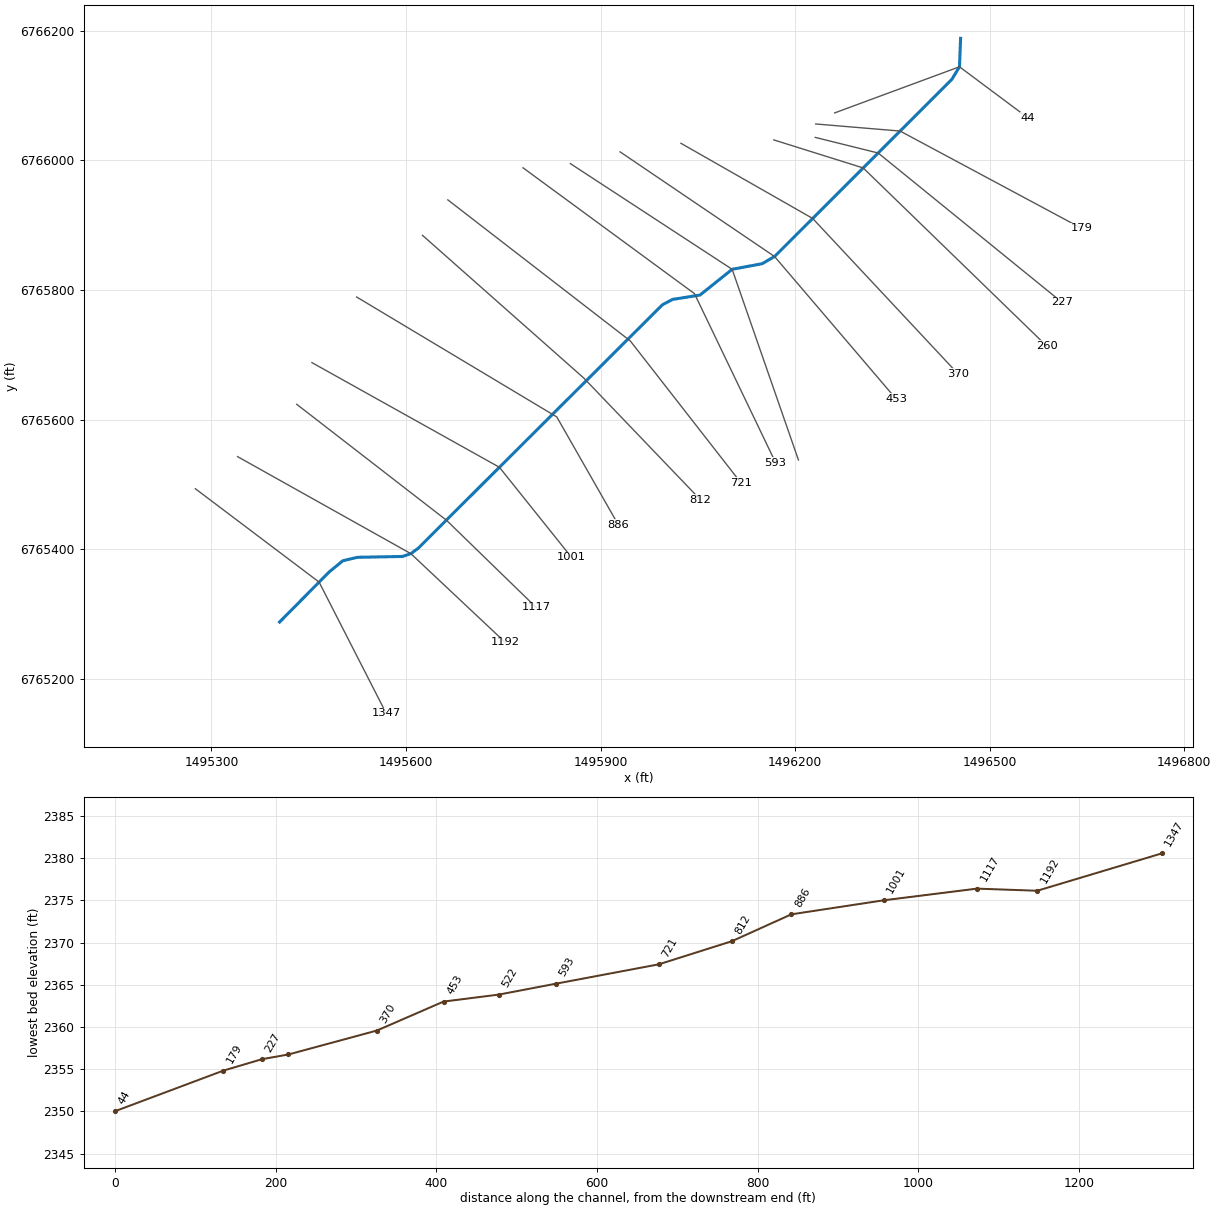
--- Elm 33.prj (project) ---

Proj Title=Elm 33 Base Level Engineering
Current Plan=p01
Default Exp/Contr=0.3,0.1
English Units
Geom File=g01
Flow File=f01
Plan File=p01
BEGIN DESCRIPTION:
Elm 33
END DESCRIPTION:

--- Elm 33.p01 (plan) ---

Plan Title=Multiple Run
Short Identifier=Multiple
Geom File=g01
Flow File=f01
Subcritical Flow
K Sum by GR= 0
Std Step Tol= 0.01
Critical Tol= 0.01
Num of Std Step Trials= 20
Max Error Tol= 0.3
Flow Tol Ratio= 0.001
Split Flow NTrial= 30
Split Flow Tol= 0.02
Split Flow Ratio= 0.02
Log Output Level= 0
Friction Slope Method= 1
Unsteady Friction Slope Method= 2
Unsteady Bridges Friction Slope Method= 1
Parabolic Critical Depth
Global Vel Dist=  1 , 1 , 1
Global Log Level= 0
CheckData=True
Encroach Param= -1, 0, 0, 0
BEGIN DESCRIPTION:
Multiple Run
END DESCRIPTION:

--- Elm 33.f01 (steady flow) ---

Flow Title=Multiple
Number of Profiles=7
Profile Names=10-year,25-year,50-year,1pct_min,100-year,1pct_plu,500-year
River Rch & RM= Elm 33,Reach-1,1347
     114     152     181     135     217     298     311
Boundary for River Rch & Prof#=Elm 33,Reach-1,1
Up Type=0
Dn Type=3
Dn Slope=0.005
Boundary for River Rch & Prof#=Elm 33,Reach-1,2
Up Type=0
Dn Type=3
Dn Slope=0.005
Boundary for River Rch & Prof#=Elm 33,Reach-1,3
Up Type=0
Dn Type=3
Dn Slope=0.005
Boundary for River Rch & Prof#=Elm 33,Reach-1,4
Up Type=0
Dn Type=3
Dn Slope=0.005
Boundary for River Rch & Prof#=Elm 33,Reach-1,5
Up Type=0
Dn Type=3
Dn Slope=0.005
Boundary for River Rch & Prof#=Elm 33,Reach-1,6
Up Type=0
Dn Type=3
Dn Slope=0.005
Boundary for River Rch & Prof#=Elm 33,Reach-1,7
Up Type=0
Dn Type=3
Dn Slope=0.005

--- Elm 33.g01 (geometry) ---

Geom Title=Existing Conditions

River Reach=Elm 33,Reach-1
Reach XY= 25
      1495405.00      6765288.00      1495443.22      6765326.62
      1495481.43      6765365.23      1495502.55      6765382.54
      1495525.05      6765387.87      1495594.52      6765389.16
      1495607.43      6765393.52      1495618.30      6765401.40
      1495681.14      6765464.04      1495743.97      6765526.68
      1495806.81      6765589.32      1495869.65      6765651.96
      1495932.48      6765714.60      1495995.32      6765777.24
      1496011.04      6765785.50      1496053.26      6765792.19
      1496102.81      6765831.90      1496148.96      6765840.50
      1496168.21      6765851.62      1496236.54      6765919.90
      1496304.87      6765988.17      1496373.20      6766056.45
      1496441.53      6766124.73      1496453.32      6766144.14
      1496455.00      6766188.00

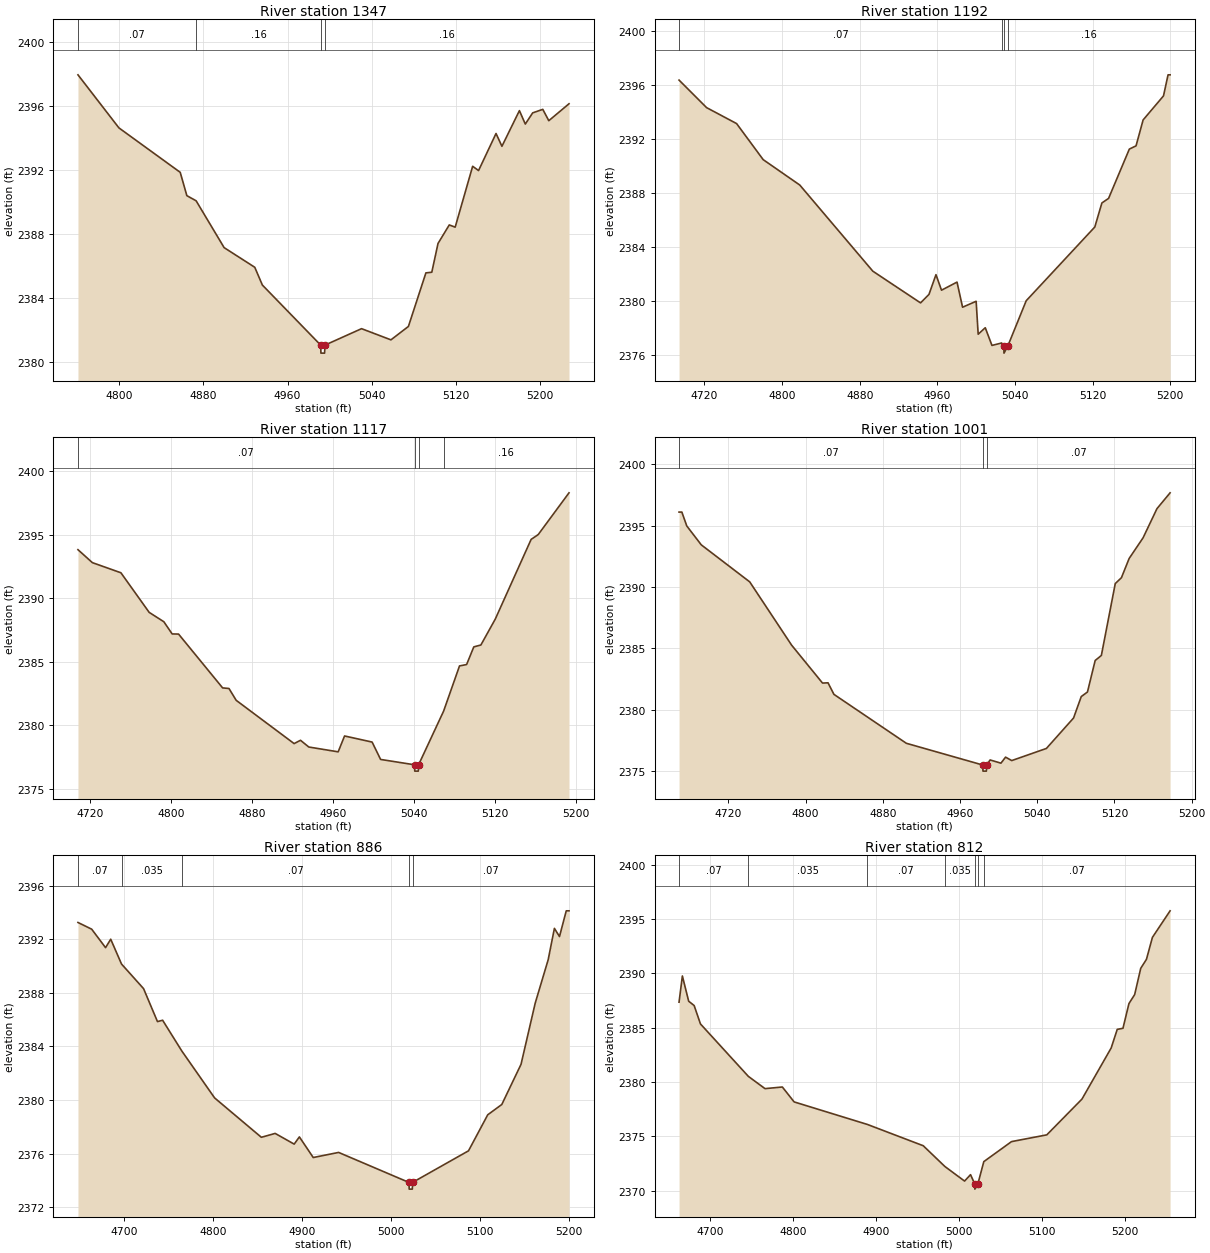
Type RM Length L Ch R = 1,1347,155,155,155
BEGIN DESCRIPTION:
elmc684
END DESCRIPTION:
XS GIS Cut Line= 3
      1495275.21      6765493.59      1495466.00      6765349.64
      1495569.46      6765147.25
#Sta/Elev= 30
  4761.0 2397.96  4799.9 2394.64  4858.1 2391.86  4864.4 2390.40  4873.2 2390.08
  4899.8 2387.15  4928.9 2385.92  4936.1 2384.81  4991.5 2381.05  4991.7 2380.55
  4995.2 2380.55  4995.5 2381.05  5030.3 2382.08  5058.2 2381.38  5074.8 2382.22
  5091.4 2385.57  5097.0 2385.61  5102.9 2387.41  5113.6 2388.57  5119.2 2388.43
  5135.8 2392.24  5141.4 2391.97  5158.0 2394.29  5163.6 2393.49  5180.2 2395.72
  5185.8 2394.88  5192.8 2395.58  5202.4 2395.80  5208.1 2395.09  5227.3 2396.15
#Mann=4,-1,0
  4761.0    0.07       0  4873.2    0.16       0  4991.5    0.07       0
  4995.5    0.16       0
Bank Sta=4991.5,4995.5
Exp/Cntr=0.3,0.1

Type RM Length L Ch R = 1,1192,75,75,75
BEGIN DESCRIPTION:
elmc683
END DESCRIPTION:
XS GIS Cut Line= 3
      1495340.25      6765543.11      1495607.43      6765393.52
      1495753.07      6765256.61
#Sta/Elev= 30
  4693.8 2396.35  4722.2 2394.31  4753.1 2393.13  4780.5 2390.46  4818.2 2388.58
  4893.5 2382.20  4942.7 2379.85  4951.4 2380.48  4958.6 2381.94  4964.3 2380.79
  4980.3 2381.39  4986.0 2379.53  5000.0 2379.97  5002.1 2377.53  5009.4 2378.01
  5016.3 2376.70  5026.3 2376.88  5028.5 2376.63  5028.7 2376.13  5032.5 2376.63
  5051.6 2380.01  5122.3 2385.47  5129.6 2387.25  5136.5 2387.59  5157.9 2391.24
  5164.8 2391.48  5172.1 2393.40  5193.1 2395.18  5197.8 2396.74  5199.9 2396.74
#Mann=4,-1,0
  4693.8    0.07       0  5026.3    0.16       0  5028.5    0.07       0
  5032.5    0.16       0
Bank Sta=5028.5,5032.5
Exp/Cntr=0.3,0.1

Type RM Length L Ch R = 1,1117,116,116,116
BEGIN DESCRIPTION:
elmc682
END DESCRIPTION:
XS GIS Cut Line= 3
      1495431.46      6765623.79      1495662.19      6765445.15
      1495800.59      6765310.64
#Sta/Elev= 30
  4708.2 2393.83  4722.4 2392.81  4750.6 2392.01  4778.5 2388.89  4793.0 2388.15
  4801.2 2387.19  4807.5 2387.18  4851.0 2382.94  4857.3 2382.89  4864.4 2381.96
  4921.6 2378.55  4927.9 2378.81  4936.1 2378.28  4965.1 2377.90  4971.4 2379.15
  4998.6 2378.67  5007.0 2377.30  5040.5 2376.88  5040.7 2376.38  5044.2 2376.38
  5044.5 2376.88  5069.2 2381.11  5084.9 2384.67  5091.9 2384.78  5099.0 2386.17
  5106.0 2386.32  5120.2 2388.36  5155.6 2394.64  5162.6 2395.02  5193.0 2398.31
#Mann=4,-1,0
  4708.2    0.07       0  5040.5    0.07       0  5044.5    0.07       0
  5069.2    0.16       0
Bank Sta=5040.5,5044.5
Exp/Cntr=0.3,0.1

Type RM Length L Ch R = 1,1001,115,115,115
BEGIN DESCRIPTION:
elmc401
END DESCRIPTION:
XS GIS Cut Line= 3
      1495454.96      6765688.02      1495743.97      6765526.68
      1495854.97      6765388.04
#Sta/Elev= 30
  4669.0 2396.12  4671.9 2396.12  4677.0 2394.99  4692.0 2393.45  4742.2 2390.43
  4785.6 2385.27  4817.6 2382.18  4823.3 2382.20  4829.4 2381.26  4904.4 2377.27
  4983.5 2375.50  4983.8 2375.00  4987.3 2375.00  4987.5 2375.50  4991.2 2375.91
  5002.4 2375.65  5007.2 2376.14  5013.6 2375.86  5049.5 2376.85  5077.6 2379.33
  5085.6 2381.08  5092.0 2381.45  5100.0 2384.02  5106.4 2384.43  5120.8 2390.29
  5127.2 2390.77  5135.2 2392.34  5149.6 2394.02  5164.0 2396.40  5177.6 2397.69
#Mann=3,-1,0
  4669.0    0.07       0  4983.5    0.07       0  4987.5    0.07       0
Bank Sta=4983.5,4987.5
Exp/Cntr=0.3,0.1

Type RM Length L Ch R = 1,886,74,74,74
BEGIN DESCRIPTION:
elmc675
END DESCRIPTION:
XS GIS Cut Line= 3
      1495523.87      6765789.19      1495832.48      6765604.28
      1495927.52      6765437.64
#Sta/Elev= 30
  4648.0 2393.25  4663.4 2392.75  4679.0 2391.37  4684.8 2392.00  4696.9 2390.15
  4721.7 2388.31  4737.3 2385.85  4743.1 2385.95  4764.7 2383.65  4801.5 2380.15
  4854.0 2377.21  4869.5 2377.50  4890.9 2376.70  4896.7 2377.24  4912.3 2375.70
  4940.8 2376.08  5019.8 2373.84  5020.1 2373.34  5023.6 2373.34  5023.8 2373.84
  5086.7 2376.20  5108.3 2378.89  5124.1 2379.66  5145.7 2382.66  5161.6 2387.22
  5176.2 2390.47  5183.2 2392.81  5188.9 2392.20  5196.5 2394.12  5199.6 2394.12
#Mann=5,-1,0
  4648.0    0.07       0  4696.9   0.035       0  4764.7    0.07       0
  5019.8    0.07       0  5023.8    0.07       0
Bank Sta=5019.8,5023.8
Exp/Cntr=0.3,0.1

Type RM Length L Ch R = 1,812,91,91,91
BEGIN DESCRIPTION:
elmc674
END DESCRIPTION:
XS GIS Cut Line= 3
      1495625.41      6765884.26      1495874.15      6765664.18
      1496053.82      6765476.69
#Sta/Elev= 30
  4662.4 2387.35  4666.4 2389.76  4674.0 2387.44  4680.6 2387.04  4688.2 2385.35
  4745.9 2380.53  4766.0 2379.40  4786.9 2379.55  4801.1 2378.18  4889.3 2376.11
  4956.7 2374.15  4982.8 2372.24  5006.5 2370.90  5013.7 2371.49  5018.6 2370.66
  5018.9 2370.16  5022.6 2370.66  5029.7 2372.69  5063.1 2374.53  5105.6 2375.15
  5148.0 2378.44  5183.2 2383.14  5190.5 2384.85  5197.4 2384.95  5204.6 2387.22
  5211.5 2388.05  5218.8 2390.46  5225.7 2391.29  5232.9 2393.31  5254.2 2395.75
#Mann=7,-1,0
  4662.4    0.07       0  4745.9   0.035       0  4889.3    0.07       0
  4982.8   0.035       0  5018.6   0.035       0  5022.6   0.035       0
  5029.7    0.07       0
Bank Sta=5018.6,5022.6
Exp/Cntr=0.3,0.1

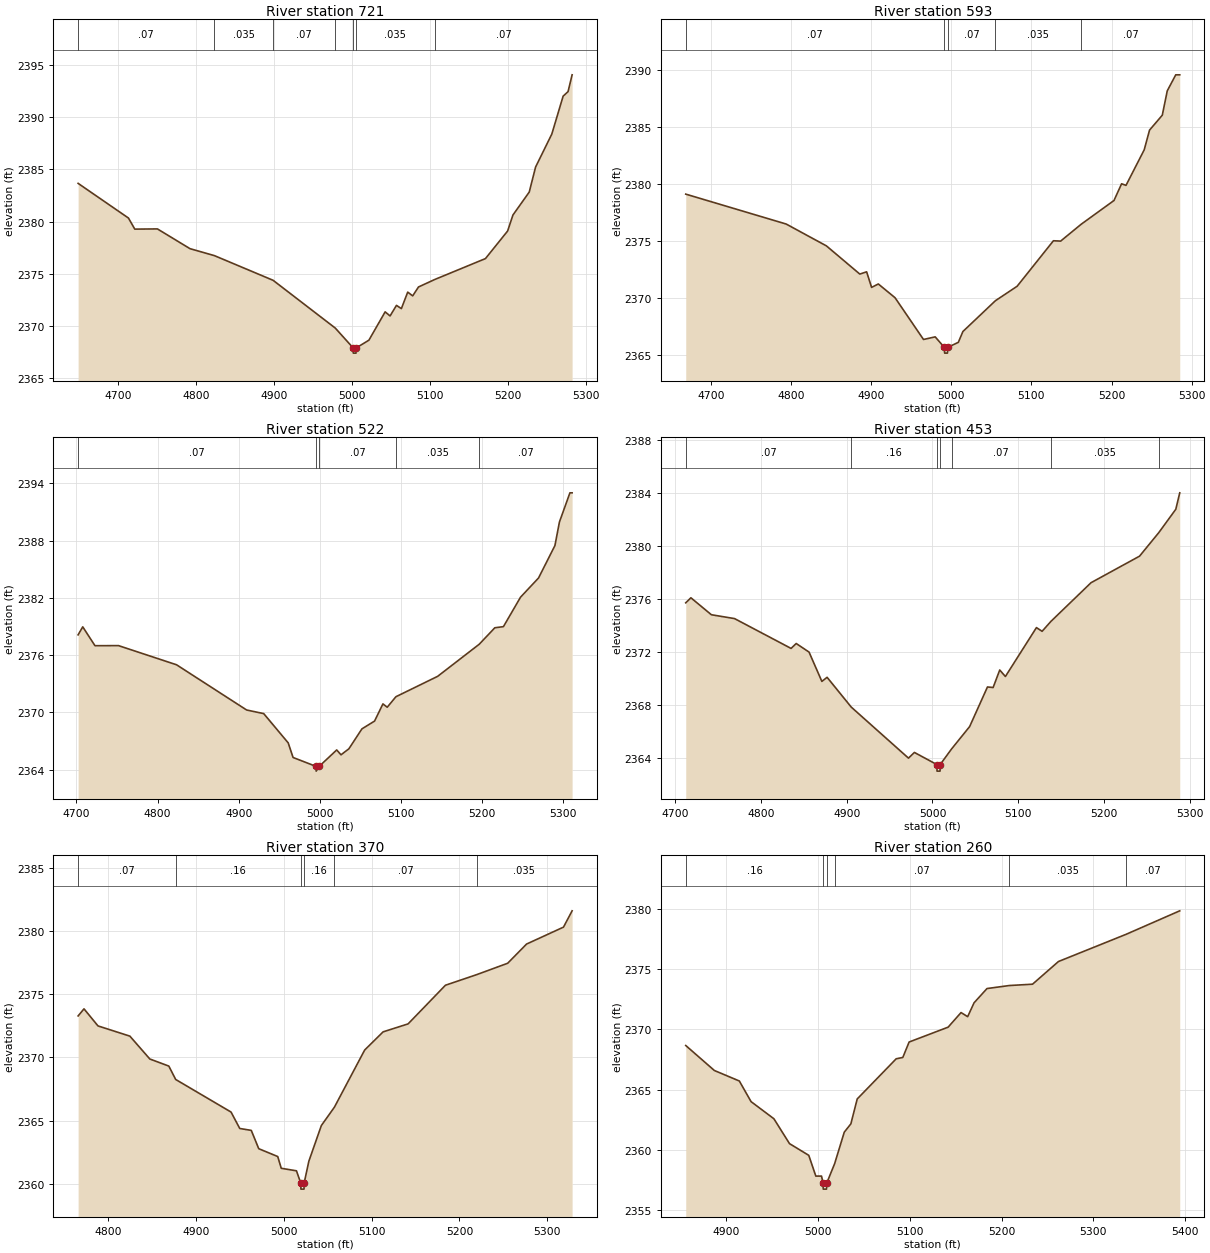
Type RM Length L Ch R = 1,721,128,128,128
BEGIN DESCRIPTION:
elmc673
END DESCRIPTION:
XS GIS Cut Line= 3
      1495664.48      6765938.94      1495945.76      6765721.47
      1496116.25      6765502.83
#Sta/Elev= 30
  4649.0 2383.67  4713.5 2380.35  4721.6 2379.29  4750.6 2379.31  4792.3 2377.42
  4823.7 2376.75  4898.8 2374.39  4978.4 2369.82  5001.3 2367.92  5001.5 2367.42
  5005.0 2367.42  5005.3 2367.92  5021.5 2368.66  5042.3 2371.37  5048.6 2370.98
  5056.8 2371.99  5063.1 2371.68  5071.2 2373.26  5077.6 2372.90  5085.0 2373.75
  5105.6 2374.46  5170.8 2376.47  5199.2 2379.11  5206.0 2380.64  5226.9 2382.84
  5235.0 2385.23  5255.8 2388.39  5270.3 2392.02  5276.6 2392.45  5281.8 2394.06
#Mann=7,-1,0
  4649.0    0.07       0  4823.7   0.035       0  4898.8    0.07       0
  4978.4   0.035       0  5001.3   0.035       0  5005.3   0.035       0
  5105.6    0.07       0
Bank Sta=5001.3,5005.3
Exp/Cntr=0.3,0.1

Type RM Length L Ch R = 1,593,71,71,71
BEGIN DESCRIPTION:
elmc672
END DESCRIPTION:
XS GIS Cut Line= 3
      1495780.43      6765988.37      1496044.72      6765794.39
      1496169.72      6765533.97
#Sta/Elev= 30
  4668.5 2379.11  4793.9 2376.48  4844.1 2374.56  4885.8 2372.08  4894.3 2372.28
  4900.5 2370.91  4908.9 2371.21  4929.8 2370.00  4965.3 2366.33  4979.9 2366.56
  4991.4 2365.63  4991.7 2365.13  4995.2 2365.13  4995.4 2365.63  5008.8 2366.08
  5014.5 2367.03  5055.1 2369.74  5082.2 2371.01  5127.5 2375.01  5136.5 2374.98
  5162.3 2376.47  5203.1 2378.55  5212.6 2380.02  5218.1 2379.88  5240.8 2383.00
  5247.5 2384.74  5263.4 2386.05  5269.6 2388.19  5280.2 2389.60  5285.2 2389.60
#Mann=5,-1,0
  4668.5    0.07       0  4991.4    0.07       0  4995.4    0.07       0
  5055.1   0.035       0  5162.3    0.07       0
Bank Sta=4991.4,4995.4
Exp/Cntr=0.3,0.1

Type RM Length L Ch R = 1,522,69,69,69
BEGIN DESCRIPTION:
elmc400
END DESCRIPTION:
XS GIS Cut Line= 3
      1495853.34      6765994.89      1496102.81      6765831.90
      1496205.01      6765537.96
#Sta/Elev= 30
  4702.0 2378.13  4707.7 2378.97  4722.8 2376.99  4751.8 2377.00  4823.4 2374.99
  4909.8 2370.25  4930.9 2369.87  4961.1 2366.80  4967.1 2365.27  4995.3 2364.34
  4995.6 2363.84  4999.3 2364.34  5020.9 2366.06  5026.2 2365.55  5035.9 2366.18
  5052.0 2368.27  5067.6 2369.09  5077.9 2370.89  5083.2 2370.54  5093.9 2371.64
  5145.4 2373.78  5196.6 2377.14  5215.9 2378.87  5226.5 2378.99  5247.6 2382.08
  5269.8 2384.09  5290.0 2387.49  5295.6 2389.97  5308.5 2393.02  5311.2 2393.02
#Mann=5,-1,0
  4702.0    0.07       0  4995.3    0.07       0  4999.3    0.07       0
  5093.9   0.035       0  5196.6    0.07       0
Bank Sta=4995.3,4999.3
Exp/Cntr=0.3,0.1

Type RM Length L Ch R = 1,453,83,83,83
BEGIN DESCRIPTION:
elmc681
END DESCRIPTION:
XS GIS Cut Line= 3
      1495930.03      6766012.98      1496168.21      6765851.62
      1496355.34      6765632.30
#Sta/Elev= 30
  4712.3 2375.71  4718.3 2376.09  4742.2 2374.81  4769.2 2374.52  4835.1 2372.27
  4841.1 2372.64  4856.1 2371.99  4871.0 2369.78  4877.1 2370.09  4905.3 2367.84
  4972.0 2363.99  4978.9 2364.42  5005.0 2363.51  5005.3 2363.01  5008.8 2363.01
  5009.0 2363.51  5022.2 2364.68  5043.3 2366.37  5064.1 2369.36  5070.7 2369.32
  5078.4 2370.64  5085.0 2370.15  5121.2 2373.84  5127.8 2373.56  5138.1 2374.31
  5184.9 2377.23  5241.4 2379.23  5263.9 2381.01  5283.7 2382.77  5288.3 2384.01
#Mann=7,-1,0
  4712.3    0.07       0  4905.3    0.16       0  5005.0    0.07       0
  5009.0    0.16       0  5022.2    0.07       0  5138.1   0.035       0
  5263.9    0.16       0
Bank Sta=5005,5009
Exp/Cntr=0.3,0.1

Type RM Length L Ch R = 1,370,110,110,110
BEGIN DESCRIPTION:
elmc680
END DESCRIPTION:
XS GIS Cut Line= 3
      1496023.88      6766026.16      1496226.96      6765910.32
      1496451.13      6765670.61
#Sta/Elev= 30
  4766.2 2373.29  4772.9 2373.85  4788.8 2372.50  4825.1 2371.69  4847.8 2369.88
  4869.4 2369.32  4877.2 2368.26  4940.2 2365.68  4950.1 2364.38  4963.2 2364.23
  4971.7 2362.78  4993.3 2362.16  4997.3 2361.23  5014.6 2361.03  5019.4 2360.08
  5019.7 2359.58  5023.2 2359.58  5023.4 2360.08  5028.7 2361.79  5042.9 2364.61
  5057.8 2366.07  5092.2 2370.59  5113.2 2372.03  5141.6 2372.66  5184.1 2375.72
  5219.7 2376.56  5254.9 2377.46  5276.4 2378.98  5318.4 2380.32  5328.2 2381.61
#Mann=6,-1,0
  4766.2    0.07       0  4877.2    0.16       0  5019.4    0.07       0
  5023.4    0.16       0  5057.8    0.07       0  5219.7   0.035       0
Bank Sta=5019.4,5023.4
Exp/Cntr=0.3,0.1

Type RM Length L Ch R = 1,260,33,33,33
BEGIN DESCRIPTION:
elmc677
END DESCRIPTION:
XS GIS Cut Line= 3
      1496167.08      6766031.38      1496304.87      6765988.17
      1496587.66      6765713.68
#Sta/Elev= 30
  4855.6 2368.65  4886.8 2366.58  4914.0 2365.71  4926.8 2364.00  4951.7 2362.58
  4968.7 2360.52  4989.7 2359.55  4997.4 2357.83  5003.6 2357.83  5005.3 2357.25
  5005.5 2356.75  5009.0 2356.75  5009.3 2357.25  5017.9 2358.86  5028.4 2361.47
  5035.6 2362.16  5042.5 2364.22  5085.0 2367.55  5092.2 2367.66  5099.1 2368.94
  5141.6 2370.17  5155.7 2371.38  5162.9 2371.04  5169.9 2372.19  5184.0 2373.37
  5208.3 2373.62  5233.6 2373.73  5261.9 2375.61  5335.5 2377.86  5394.1 2379.81
#Mann=6,-1,0
  4855.6    0.16       0  5005.3    0.07       0  5009.3    0.16       0
  5017.9    0.07       0  5208.3   0.035       0  5335.5    0.07       0
Bank Sta=5005.3,5009.3
Exp/Cntr=0.3,0.1

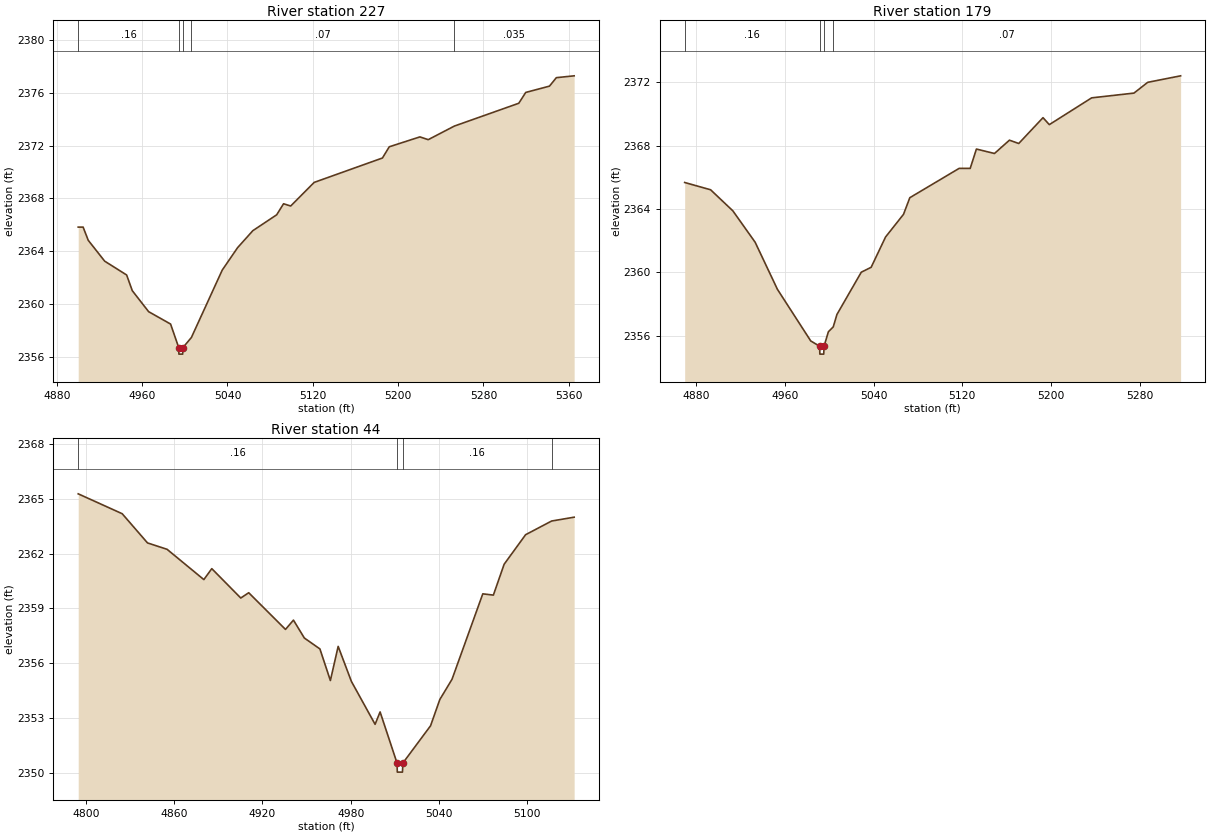
Type RM Length L Ch R = 1,227,48,48,48
BEGIN DESCRIPTION:
elmc679
END DESCRIPTION:
XS GIS Cut Line= 3
      1496230.95      6766035.26      1496327.91      6766011.20
      1496611.21      6765781.05
#Sta/Elev= 30
  4900.1 2365.82  4904.7 2365.82  4909.5 2364.82  4924.9 2363.24  4945.5 2362.19
  4950.8 2361.00  4966.1 2359.41  4986.7 2358.47  4994.3 2356.69  4994.5 2356.19
  4998.0 2356.19  4998.3 2356.69  5006.2 2357.45  5035.1 2362.56  5049.5 2364.26
  5063.8 2365.55  5086.1 2366.75  5092.6 2367.59  5099.3 2367.42  5121.3 2369.21
  5185.3 2371.06  5191.7 2371.91  5220.4 2372.66  5228.2 2372.45  5252.7 2373.48
  5313.1 2375.21  5319.6 2376.03  5341.9 2376.51  5348.3 2377.15  5365.0 2377.29
#Mann=5,-1,0
  4900.1    0.16       0  4994.3    0.07       0  4998.3    0.16       0
  5006.2    0.07       0  5252.7   0.035       0
Bank Sta=4994.3,4998.3
Exp/Cntr=0.3,0.1

Type RM Length L Ch R = 1,179,135,135,135
BEGIN DESCRIPTION:
elmc678
END DESCRIPTION:
XS GIS Cut Line= 3
      1496231.64      6766055.97      1496361.78      6766045.04
      1496641.18      6765895.29
#Sta/Elev= 30
  4869.4 2365.67  4892.8 2365.21  4912.9 2363.88  4933.0 2361.90  4953.1 2358.93
  4983.2 2355.67  4991.2 2355.34  4991.4 2354.84  4994.9 2354.84  4995.2 2355.34
  4999.1 2356.25  5003.5 2356.56  5006.8 2357.34  5028.8 2360.01  5037.7 2360.32
  5050.7 2362.23  5066.9 2363.66  5072.6 2364.71  5117.1 2366.56  5127.1 2366.56
  5132.7 2367.78  5149.0 2367.50  5162.5 2368.34  5170.9 2368.13  5192.8 2369.76
  5198.5 2369.32  5236.7 2371.01  5274.9 2371.31  5287.3 2371.99  5317.0 2372.40
#Mann=4,-1,0
  4869.4    0.16       0  4991.2    0.07       0  4995.2    0.16       0
  5003.5    0.07       0
Bank Sta=4991.2,4995.2
Exp/Cntr=0.3,0.1

Type RM Length L Ch R = 1,44,0,0,0
BEGIN DESCRIPTION:
elmc676
END DESCRIPTION:
XS GIS Cut Line= 3
      1496260.84      6766073.02      1496453.32      6766144.14
      1496559.02      6766065.24
#Sta/Elev= 30
  4794.8 2365.28  4824.7 2364.19  4841.9 2362.59  4855.2 2362.24  4880.2 2360.58
  4885.6 2361.18  4905.3 2359.57  4910.7 2359.86  4935.7 2357.85  4941.1 2358.36
  4948.5 2357.38  4959.1 2356.78  4966.2 2355.05  4971.5 2356.92  4980.5 2355.00
  4996.6 2352.65  5000.0 2353.33  5011.5 2350.53  5011.7 2350.03  5015.2 2350.03
  5015.5 2350.53  5034.3 2352.57  5040.6 2354.01  5048.9 2355.12  5069.8 2359.80
  5077.0 2359.73  5084.3 2361.42  5098.9 2363.04  5116.6 2363.79  5131.9 2364.00
#Mann=4,-1,0
  4794.8    0.16       0  5011.5    0.07       0  5015.5    0.16       0
  5116.6    0.07       0
Bank Sta=5011.5,5015.5
Exp/Cntr=0.3,0.1

Chan Stop Cuts=-1