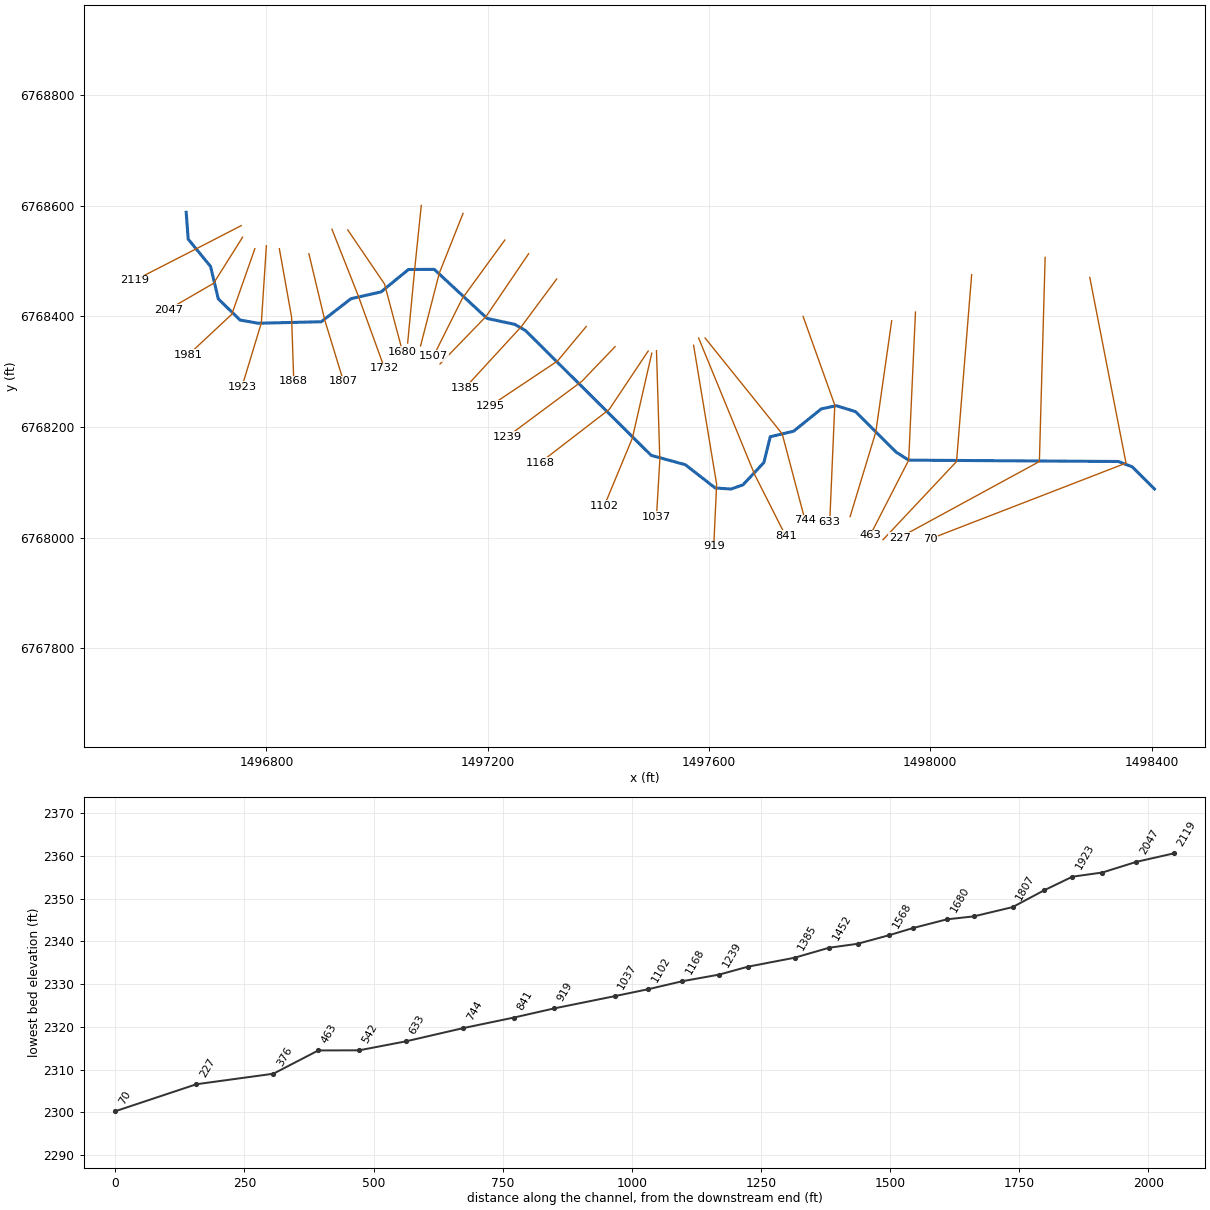
--- Elm 34.prj (project) ---

Proj Title=Elm 34 Base Level Engineering
Current Plan=p01
Default Exp/Contr=0.3,0.1
English Units
Geom File=g01
Flow File=f01
Plan File=p01
BEGIN DESCRIPTION:
Elm 34
END DESCRIPTION:

--- Elm 34.p01 (plan) ---

Plan Title=Multiple Run
Short Identifier=Multiple
Geom File=g01
Flow File=f01
Subcritical Flow
K Sum by GR= 0
Std Step Tol= 0.01
Critical Tol= 0.01
Num of Std Step Trials= 20
Max Error Tol= 0.3
Flow Tol Ratio= 0.001
Split Flow NTrial= 30
Split Flow Tol= 0.02
Split Flow Ratio= 0.02
Log Output Level= 0
Friction Slope Method= 1
Unsteady Friction Slope Method= 2
Unsteady Bridges Friction Slope Method= 1
Parabolic Critical Depth
Global Vel Dist=  1 , 1 , 1
Global Log Level= 0
CheckData=True
Encroach Param= -1, 0, 0, 0
BEGIN DESCRIPTION:
Multiple Run
END DESCRIPTION:

--- Elm 34.f01 (steady flow) ---

Flow Title=Multiple
Number of Profiles=7
Profile Names=10-year,25-year,50-year,1pct_min,100-year,1pct_plu,500-year
River Rch & RM= Elm 34,Reach-1,2119
     132     178     215     162     259     356     379
Boundary for River Rch & Prof#=Elm 34,Reach-1,1
Up Type=0
Dn Type=3
Dn Slope=0.005
Boundary for River Rch & Prof#=Elm 34,Reach-1,2
Up Type=0
Dn Type=3
Dn Slope=0.005
Boundary for River Rch & Prof#=Elm 34,Reach-1,3
Up Type=0
Dn Type=3
Dn Slope=0.005
Boundary for River Rch & Prof#=Elm 34,Reach-1,4
Up Type=0
Dn Type=3
Dn Slope=0.005
Boundary for River Rch & Prof#=Elm 34,Reach-1,5
Up Type=0
Dn Type=3
Dn Slope=0.005
Boundary for River Rch & Prof#=Elm 34,Reach-1,6
Up Type=0
Dn Type=3
Dn Slope=0.005
Boundary for River Rch & Prof#=Elm 34,Reach-1,7
Up Type=0
Dn Type=3
Dn Slope=0.005

--- Elm 34.g01 (geometry) ---

Geom Title=Existing Conditions

River Reach=Elm 34,Reach-1
Reach XY= 30
      1496655.00      6768588.00      1496658.60      6768539.49
      1496699.01      6768490.21      1496712.99      6768431.60
      1496752.30      6768393.35      1496784.77      6768387.51
      1496899.07      6768390.23      1496952.82      6768431.89
      1497007.20      6768444.16      1497056.74      6768484.69
      1497103.36      6768484.86      1497198.96      6768396.18
      1497248.95      6768385.47      1497268.21      6768374.37
      1497495.32      6768148.76      1497557.19      6768131.82
      1497611.16      6768089.75      1497639.78      6768087.91
      1497661.32      6768095.41      1497699.11      6768135.72
      1497710.62      6768182.38      1497752.90      6768192.40
      1497802.78      6768232.70      1497830.02      6768238.51
      1497864.67      6768227.79      1497938.25      6768154.47
      1497960.86      6768140.07      1498339.85      6768137.64
      1498364.98      6768127.95      1498405.00      6768088.00

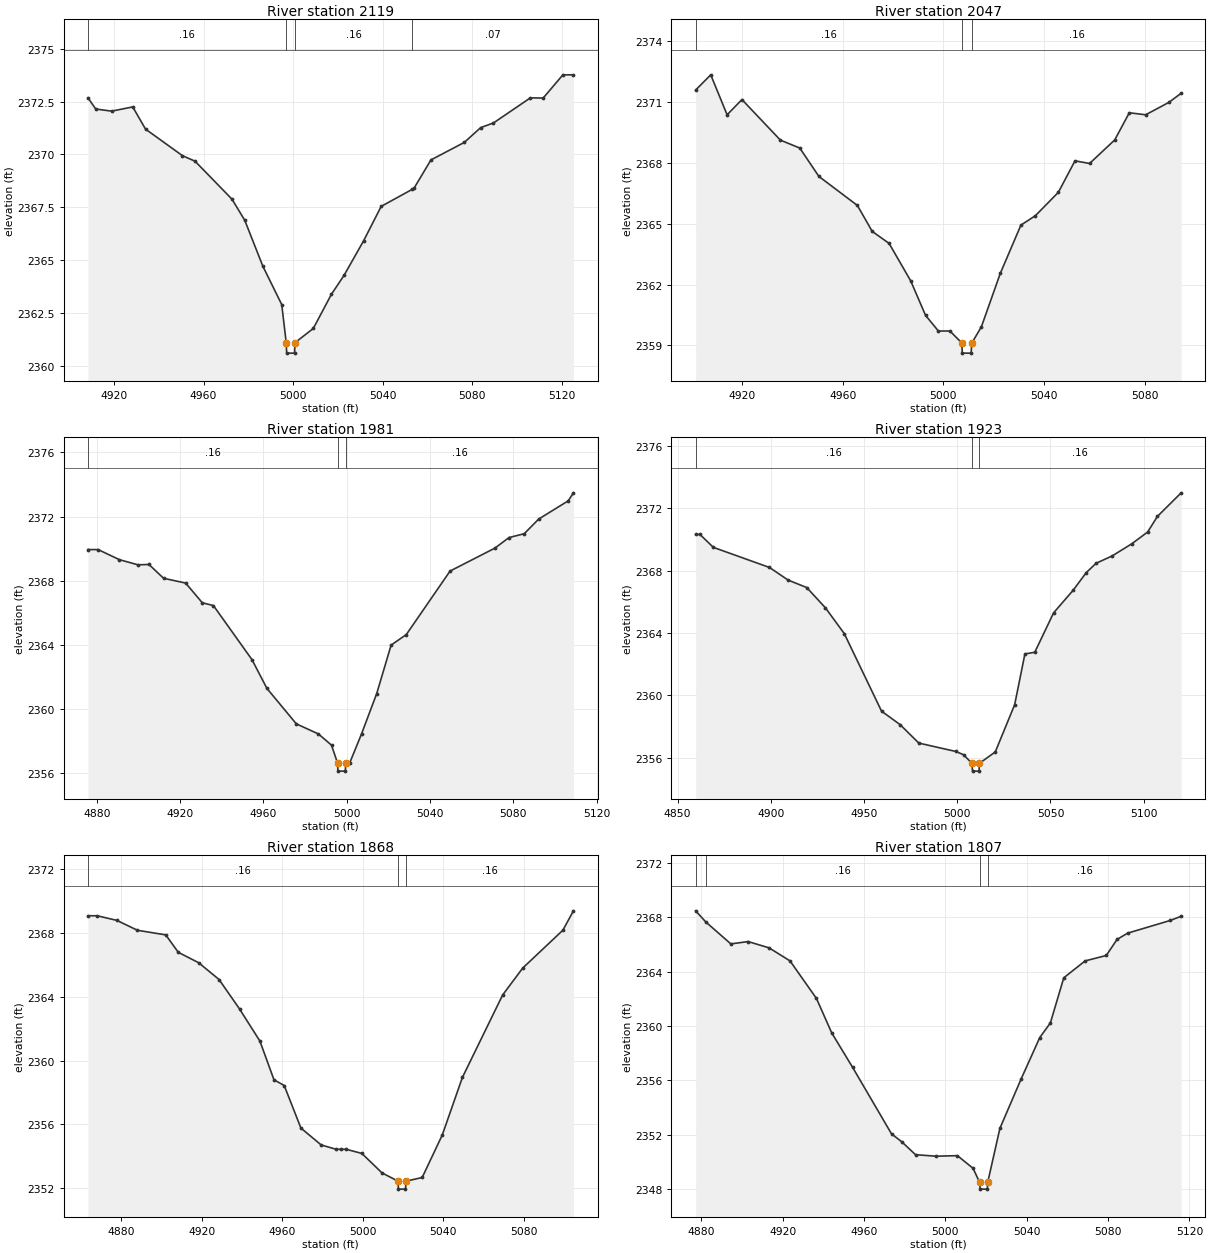
Type RM Length L Ch R = 1,2119,72,72,72
BEGIN DESCRIPTION:
elmc709
END DESCRIPTION:
XS GIS Cut Line= 3
      1496754.39      6768563.94      1496672.98      6768521.95
      1496561.62      6768464.95
#Sta/Elev= 30
  4908.4 2372.68  4911.9 2372.15  4919.0 2372.05  4928.4 2372.25  4934.1 2371.20
  4950.6 2369.94  4956.2 2369.68  4972.7 2367.88  4978.4 2366.88  4986.5 2364.70
  4994.9 2362.89  4996.9 2361.09  4997.1 2360.59  5000.6 2360.59  5000.9 2361.09
  5009.0 2361.76  5017.1 2363.38  5022.7 2364.27  5031.4 2365.90  5039.3 2367.54
  5053.2 2368.35  5053.9 2368.39  5061.5 2369.74  5076.4 2370.57  5083.7 2371.27
  5089.4 2371.49  5105.9 2372.68  5111.6 2372.67  5120.4 2373.77  5125.1 2373.77
#Mann=4,-1,0
  4908.4    0.16       0  4996.9    0.07       0  5000.9    0.16       0
  5053.2    0.07       0
Bank Sta=4996.9,5000.9
Exp/Cntr=0.3,0.1

Type RM Length L Ch R = 1,2047,66,66,66
BEGIN DESCRIPTION:
elmc708
END DESCRIPTION:
XS GIS Cut Line= 3
      1496756.95      6768543.07      1496704.52      6768459.69
      1496622.77      6768412.29
#Sta/Elev= 30
  4901.5 2371.59  4907.5 2372.34  4914.0 2370.37  4919.9 2371.12  4935.2 2369.12
  4942.9 2368.73  4950.5 2367.33  4965.8 2365.90  4971.7 2364.62  4978.4 2364.03
  4987.0 2362.18  4992.9 2360.48  4998.0 2359.71  5002.6 2359.71  5007.3 2359.12
  5007.5 2358.62  5011.0 2358.62  5011.3 2359.12  5015.1 2359.92  5022.6 2362.55
  5030.8 2364.93  5036.6 2365.40  5045.7 2366.55  5052.3 2368.10  5058.1 2367.97
  5068.1 2369.13  5073.9 2370.47  5080.4 2370.37  5089.6 2370.98  5094.5 2371.43
#Mann=3,-1,0
  4901.5    0.16       0  5007.3    0.07       0  5011.3    0.16       0
Bank Sta=5007.3,5011.3
Exp/Cntr=0.3,0.1

Type RM Length L Ch R = 1,1981,58,58,58
BEGIN DESCRIPTION:
elmc703
END DESCRIPTION:
XS GIS Cut Line= 3
      1496779.11      6768522.29      1496737.43      6768403.76
      1496658.99      6768330.46
#Sta/Elev= 30
  4875.8 2369.94  4880.7 2369.94  4890.9 2369.31  4899.8 2368.99  4905.1 2369.01
  4912.1 2368.15  4922.7 2367.85  4930.7 2366.62  4936.0 2366.45  4954.5 2363.08
  4961.7 2361.28  4975.8 2359.07  4986.4 2358.44  4992.7 2357.74  4995.6 2356.62
  4995.8 2356.12  4999.3 2356.12  4999.6 2356.62  5001.4 2356.62  5007.1 2358.44
  5014.4 2360.96  5021.3 2363.98  5028.6 2364.64  5049.6 2368.60  5071.1 2370.03
  5077.9 2370.69  5085.2 2370.93  5092.1 2371.84  5106.3 2372.98  5108.8 2373.48
#Mann=3,-1,0
  4875.8    0.16       0  4995.6    0.07       0  4999.6    0.16       0
Bank Sta=4995.6,4999.6
Exp/Cntr=0.3,0.1

Type RM Length L Ch R = 1,1923,55,55,55
BEGIN DESCRIPTION:
elmc702
END DESCRIPTION:
XS GIS Cut Line= 3
      1496799.93      6768527.49      1496790.81      6768388.14
      1496755.76      6768272.59
#Sta/Elev= 30
  4859.7 2370.33  4862.0 2370.33  4869.2 2369.50  4899.3 2368.21  4909.3 2367.40
  4919.3 2366.92  4929.3 2365.62  4939.4 2363.97  4959.4 2358.99  4969.4 2358.12
  4979.4 2356.94  4999.3 2356.40  5003.4 2356.19  5007.9 2355.64  5008.2 2355.14
  5011.7 2355.14  5011.9 2355.64  5020.4 2356.37  5030.8 2359.40  5036.3 2362.66
  5041.6 2362.77  5051.7 2365.30  5062.2 2366.75  5069.2 2367.88  5074.5 2368.48
  5083.1 2368.95  5093.5 2369.72  5102.1 2370.48  5107.4 2371.49  5120.1 2373.00
#Mann=3,-1,0
  4859.7    0.16       0  5007.9    0.07       0  5011.9    0.16       0
Bank Sta=5007.9,5011.9
Exp/Cntr=0.3,0.1

Type RM Length L Ch R = 1,1868,61,61,61
BEGIN DESCRIPTION:
elmc701
END DESCRIPTION:
XS GIS Cut Line= 3
      1496823.37      6768522.20      1496845.50      6768398.55
      1496849.40      6768282.83
#Sta/Elev= 30
  4863.4 2369.09  4868.0 2369.09  4877.8 2368.80  4888.0 2368.18  4902.1 2367.89
  4908.3 2366.80  4918.5 2366.14  4928.6 2365.09  4938.8 2363.24  4948.9 2361.23
  4955.9 2358.80  4961.0 2358.44  4969.3 2355.77  4979.4 2354.71  4986.8 2354.44
  4989.0 2354.44  4991.8 2354.44  4999.6 2354.18  5009.6 2352.96  5017.6 2352.44
  5017.8 2351.94  5021.3 2351.94  5021.6 2352.44  5029.6 2352.67  5039.6 2355.34
  5049.6 2358.95  5069.6 2364.12  5079.6 2365.81  5099.6 2368.19  5104.8 2369.40
#Mann=3,-1,0
  4863.4    0.16       0  5017.6    0.07       0  5021.6    0.16       0
Bank Sta=5017.6,5021.6
Exp/Cntr=0.3,0.1

Type RM Length L Ch R = 1,1807,75,75,75
BEGIN DESCRIPTION:
elmc700
END DESCRIPTION:
XS GIS Cut Line= 3
      1496876.76      6768513.09      1496905.40      6768393.34
      1496939.20      6768282.82
#Sta/Elev= 30
  4877.2 2368.46  4882.2 2367.64  4894.5 2366.03  4903.0 2366.20  4913.3 2365.74
  4923.6 2364.78  4936.6 2362.02  4944.1 2359.49  4954.4 2356.95  4973.5 2352.07
  4978.6 2351.48  4985.3 2350.54  4995.4 2350.43  5005.9 2350.47  5013.6 2349.54
  5016.8 2348.51  5017.1 2348.01  5020.6 2348.01  5020.8 2348.51  5026.8 2352.48
  5037.3 2356.13  5046.4 2359.15  5051.6 2360.22  5058.2 2363.54  5068.7 2364.78
  5079.1 2365.18  5084.4 2366.36  5089.6 2366.82  5110.5 2367.75  5115.9 2368.06
#Mann=4,-1,0
  4877.2    0.07       0  4882.2    0.16       0  5016.8    0.07       0
  5020.8    0.16       0
Bank Sta=5016.8,5020.8
Exp/Cntr=0.3,0.1

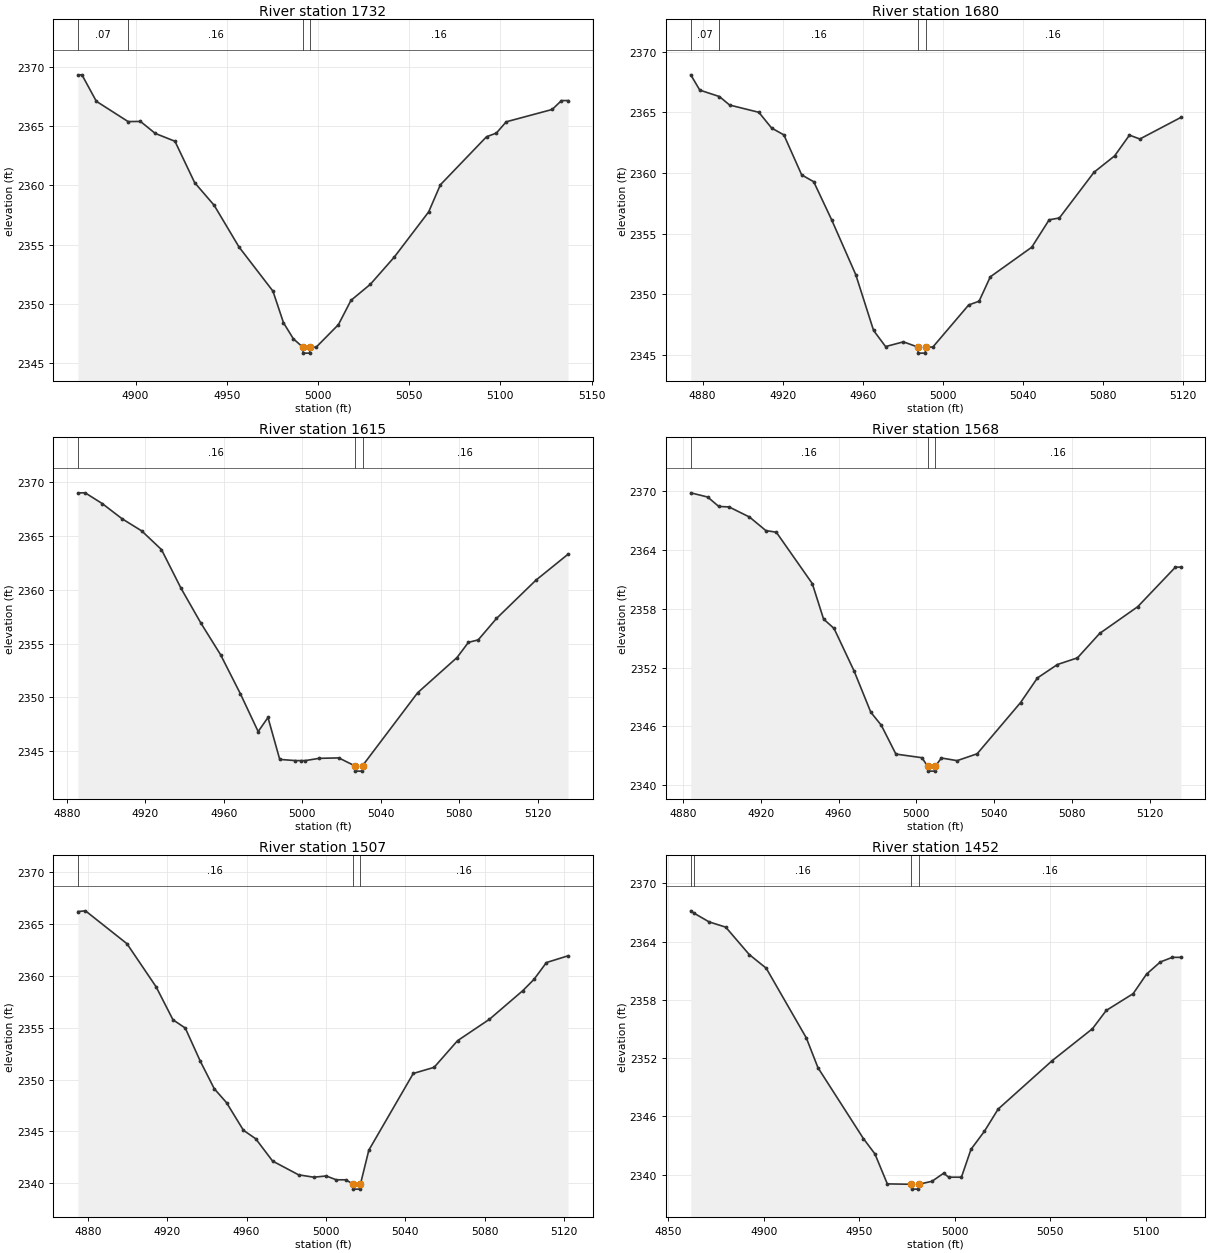
Type RM Length L Ch R = 1,1732,52,52,52
BEGIN DESCRIPTION:
elmc699
END DESCRIPTION:
XS GIS Cut Line= 3
      1496918.41      6768557.43      1496965.29      6768438.92
      1497013.46      6768306.14
#Sta/Elev= 30
  4868.4 2369.31  4870.6 2369.31  4878.5 2367.08  4895.9 2365.37  4902.7 2365.38
  4910.8 2364.37  4921.6 2363.71  4932.4 2360.22  4943.1 2358.31  4956.7 2354.80
  4975.3 2351.08  4981.1 2348.41  4986.5 2347.06  4991.7 2346.35  4991.9 2345.85
  4995.4 2345.85  4995.7 2346.35  4999.0 2346.35  5011.2 2348.25  5018.1 2350.30
  5028.7 2351.65  5041.8 2353.94  5060.7 2357.76  5067.1 2360.04  5092.4 2364.09
  5097.8 2364.40  5103.2 2365.35  5128.4 2366.39  5133.5 2367.14  5137.1 2367.14
#Mann=4,-1,0
  4868.4    0.07       0  4895.9    0.16       0  4991.7    0.07       0
  4995.7    0.16       0
Bank Sta=4991.7,4995.7
Exp/Cntr=0.3,0.1

Type RM Length L Ch R = 1,1680,65,65,65
BEGIN DESCRIPTION:
elmc698
END DESCRIPTION:
XS GIS Cut Line= 3
      1496947.05      6768556.12      1497013.47      6768458.45
      1497046.03      6768336.02
#Sta/Elev= 30
  4874.1 2368.10  4878.6 2366.84  4888.4 2366.31  4893.5 2365.61  4908.1 2365.01
  4914.5 2363.71  4920.6 2363.15  4929.5 2359.85  4935.5 2359.29  4944.4 2356.17
  4956.5 2351.63  4965.4 2347.03  4971.4 2345.70  4980.3 2346.09  4987.5 2345.66
  4987.7 2345.16  4991.2 2345.16  4991.5 2345.66  4995.0 2345.66  5012.9 2349.13
  5018.1 2349.44  5023.7 2351.45  5044.4 2353.89  5053.1 2356.15  5058.2 2356.30
  5075.5 2360.07  5085.8 2361.42  5093.2 2363.13  5098.4 2362.81  5118.9 2364.59
#Mann=4,-1,0
  4874.1    0.07       0  4888.4    0.16       0  4987.5    0.07       0
  4991.5    0.16       0
Bank Sta=4987.5,4991.5
Exp/Cntr=0.3,0.1

Type RM Length L Ch R = 1,1615,47,47,47
BEGIN DESCRIPTION:
elmc695
END DESCRIPTION:
XS GIS Cut Line= 3
      1497079.87      6768600.34      1497068.16      6768487.09
      1497055.26      6768351.66
#Sta/Elev= 29
  4885.6 2369.03  4889.3 2369.03  4898.0 2368.03  4908.1 2366.62  4918.1 2365.49
  4928.2 2363.75  4938.2 2360.14  4948.3 2356.91  4958.3 2353.98  4968.4 2350.35
  4977.5 2346.82  4982.5 2348.13  4988.5 2344.23  4996.5 2344.12  4999.5 2344.12
  5001.5 2344.12  5008.6 2344.33  5018.6 2344.37  5026.7 2343.64  5026.9 2343.14
  5030.4 2343.14  5030.7 2343.64  5058.8 2350.43  5078.9 2353.71  5084.7 2355.12
  5089.7 2355.35  5099.0 2357.34  5119.1 2360.90  5135.5 2363.32
#Mann=3,-1,0
  4885.6    0.16       0  5026.7    0.07       0  5030.7    0.16       0
Bank Sta=5026.7,5030.7
Exp/Cntr=0.3,0.1

Type RM Length L Ch R = 1,1568,61,61,61
BEGIN DESCRIPTION:
elmc697
END DESCRIPTION:
XS GIS Cut Line= 3
      1497155.41      6768586.07      1497112.43      6768477.98
      1497078.58      6768346.49
#Sta/Elev= 30
  4884.0 2369.84  4892.7 2369.41  4898.4 2368.45  4903.7 2368.40  4914.2 2367.37
  4922.6 2365.99  4928.0 2365.82  4946.5 2360.58  4952.3 2356.96  4957.7 2356.00
  4968.0 2351.66  4976.6 2347.45  4982.0 2346.12  4989.5 2343.18  5002.9 2342.81
  5005.8 2341.94  5006.0 2341.44  5009.5 2341.44  5009.8 2341.94  5012.9 2342.78
  5021.0 2342.51  5031.3 2343.21  5053.6 2348.43  5062.3 2350.95  5072.6 2352.32
  5082.9 2353.00  5094.3 2355.49  5113.9 2358.22  5133.3 2362.26  5136.1 2362.26
#Mann=3,-1,0
  4884.0    0.16       0  5005.8    0.07       0  5009.8    0.16       0
Bank Sta=5005.8,5009.8
Exp/Cntr=0.3,0.1

Type RM Length L Ch R = 1,1507,55,55,55
BEGIN DESCRIPTION:
elmc696
END DESCRIPTION:
XS GIS Cut Line= 3
      1497230.94      6768537.91      1497154.09      6768432.41
      1497102.00      6768328.22
#Sta/Elev= 30
  4875.0 2366.21  4878.8 2366.28  4899.7 2363.11  4914.4 2358.95  4922.9 2355.77
  4929.1 2354.97  4936.7 2351.76  4943.7 2349.12  4949.9 2347.77  4958.4 2345.11
  4964.6 2344.29  4973.1 2342.14  4986.2 2340.81  4993.9 2340.58  5000.1 2340.70
  5005.2 2340.33  5010.1 2340.33  5013.4 2339.93  5013.6 2339.43  5017.1 2339.43
  5017.4 2339.93  5021.6 2343.19  5044.0 2350.59  5054.5 2351.18  5066.3 2353.75
  5082.4 2355.82  5099.2 2358.58  5104.8 2359.66  5111.1 2361.29  5122.0 2361.94
#Mann=3,-1,0
  4875.0    0.16       0  5013.4    0.07       0  5017.4    0.16       0
Bank Sta=5013.4,5017.4
Exp/Cntr=0.3,0.1

Type RM Length L Ch R = 1,1452,67,67,67
BEGIN DESCRIPTION:
elmc694
END DESCRIPTION:
XS GIS Cut Line= 3
      1497273.90      6768513.16      1497197.06      6768399.85
      1497113.73      6768313.92
#Sta/Elev= 30
  4861.8 2367.17  4863.4 2366.94  4871.4 2366.03  4880.1 2365.49  4892.4 2362.67
  4901.3 2361.26  4922.3 2354.08  4928.4 2351.01  4952.2 2343.71  4958.2 2342.14
  4964.7 2339.05  4977.2 2339.01  4977.5 2338.51  4981.0 2338.51  4981.2 2339.01
  4988.1 2339.32  4994.2 2340.15  4996.8 2339.74  5003.5 2339.74  5008.5 2342.61
  5015.5 2344.46  5022.7 2346.75  5051.0 2351.74  5072.1 2355.03  5079.3 2356.91
  5093.4 2358.64  5100.4 2360.65  5107.6 2361.90  5113.9 2362.38  5118.4 2362.38
#Mann=4,-1,0
  4861.8    0.07       0  4863.4    0.16       0  4977.2    0.07       0
  4981.2    0.16       0
Bank Sta=4977.2,4981.2
Exp/Cntr=0.3,0.1

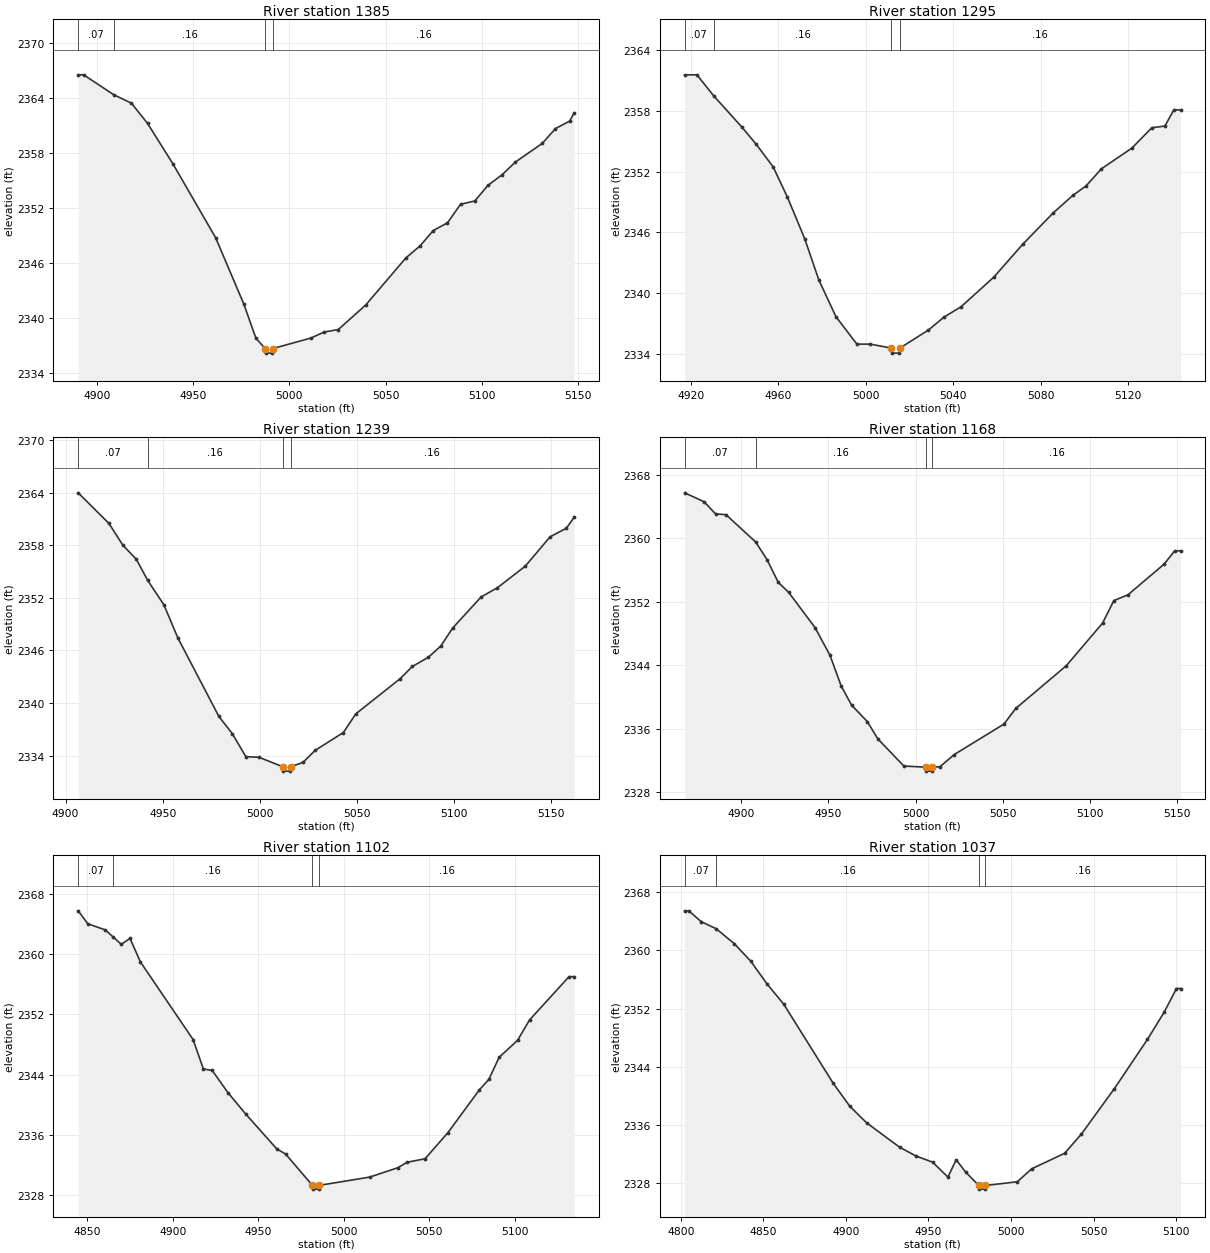
Type RM Length L Ch R = 1,1385,90,90,90
BEGIN DESCRIPTION:
elmc693
END DESCRIPTION:
XS GIS Cut Line= 3
      1497324.66      6768467.55      1497260.87      6768381.63
      1497158.99      6768270.73
#Sta/Elev= 30
  4890.3 2366.57  4893.1 2366.57  4908.8 2364.39  4917.9 2363.48  4926.3 2361.27
  4939.6 2356.81  4961.7 2348.77  4976.3 2341.54  4982.6 2337.80  4987.4 2336.67
  4987.6 2336.17  4991.1 2336.17  4991.4 2336.67  5011.2 2337.82  5018.0 2338.47
  5025.4 2338.75  5039.6 2341.42  5060.5 2346.57  5067.9 2347.89  5074.7 2349.56
  5082.1 2350.40  5088.9 2352.43  5096.3 2352.79  5103.1 2354.49  5110.5 2355.66
  5117.3 2357.03  5131.4 2359.09  5138.2 2360.70  5145.6 2361.52  5147.9 2362.42
#Mann=4,-1,0
  4890.3    0.07       0  4908.8    0.16       0  4987.4    0.07       0
  4991.4    0.16       0
Bank Sta=4987.4,4991.4
Exp/Cntr=0.3,0.1

Type RM Length L Ch R = 1,1295,56,56,56
BEGIN DESCRIPTION:
elmc691
END DESCRIPTION:
XS GIS Cut Line= 3
      1497378.05      6768381.62      1497325.97      6768319.13
      1497204.87      6768238.39
#Sta/Elev= 30
  4917.1 2361.57  4922.7 2361.57  4930.4 2359.49  4943.3 2356.40  4949.8 2354.72
  4957.6 2352.47  4964.1 2349.49  4972.0 2345.39  4978.5 2341.30  4986.3 2337.68
  4995.9 2334.97  5002.0 2334.97  5011.6 2334.58  5011.8 2334.08  5015.3 2334.08
  5015.6 2334.58  5028.6 2336.36  5035.7 2337.63  5043.6 2338.67  5058.6 2341.60
  5071.7 2344.82  5085.7 2347.93  5094.7 2349.66  5100.7 2350.59  5107.8 2352.29
  5121.7 2354.33  5130.8 2356.34  5136.8 2356.51  5140.9 2358.11  5144.0 2358.11
#Mann=4,-1,0
  4917.1    0.07       0  4930.4    0.16       0  5011.6    0.07       0
  5015.6    0.16       0
Bank Sta=5011.6,5015.6
Exp/Cntr=0.3,0.1

Type RM Length L Ch R = 1,1239,71,71,71
BEGIN DESCRIPTION:
elmc692
END DESCRIPTION:
XS GIS Cut Line= 3
      1497430.14      6768345.17      1497370.24      6768282.67
      1497234.80      6768182.05
#Sta/Elev= 30
  4906.5 2364.00  4922.3 2360.51  4929.5 2358.02  4936.4 2356.42  4942.3 2353.99
  4950.6 2351.22  4957.8 2347.43  4978.9 2338.47  4985.8 2336.51  4992.8 2333.87
  4999.6 2333.80  5011.8 2332.72  5012.0 2332.22  5015.5 2332.22  5015.8 2332.72
  5022.2 2333.21  5028.4 2334.58  5043.0 2336.63  5049.4 2338.76  5072.2 2342.77
  5078.5 2344.17  5086.8 2345.23  5093.1 2346.49  5099.3 2348.57  5113.9 2352.11
  5122.3 2353.16  5136.6 2355.62  5149.4 2358.97  5157.8 2359.96  5161.8 2361.21
#Mann=4,-1,0
  4906.5    0.07       0  4942.3    0.16       0  5011.8    0.07       0
  5015.8    0.16       0
Bank Sta=5011.8,5015.8
Exp/Cntr=0.3,0.1

Type RM Length L Ch R = 1,1168,66,66,66
BEGIN DESCRIPTION:
elmc689
END DESCRIPTION:
XS GIS Cut Line= 3
      1497490.03      6768337.35      1497419.72      6768231.89
      1497294.71      6768135.52
#Sta/Elev= 30
  4867.5 2365.71  4878.7 2364.58  4885.2 2363.06  4891.2 2362.96  4908.2 2359.53
  4914.8 2357.29  4921.2 2354.44  4927.2 2353.18  4942.3 2348.75  4950.9 2345.26
  4957.3 2341.40  4963.3 2338.98  4972.3 2336.92  4978.3 2334.75  4993.3 2331.32
  5005.7 2331.18  5005.9 2330.68  5009.4 2330.68  5009.7 2331.18  5014.0 2331.23
  5022.2 2332.77  5050.7 2336.60  5057.5 2338.57  5086.5 2343.95  5107.3 2349.31
  5113.8 2352.15  5121.8 2352.86  5142.6 2356.73  5148.7 2358.41  5152.1 2358.41
#Mann=4,-1,0
  4867.5    0.07       0  4908.2    0.16       0  5005.7    0.07       0
  5009.7    0.16       0
Bank Sta=5005.7,5009.7
Exp/Cntr=0.3,0.1

Type RM Length L Ch R = 1,1102,65,65,65
BEGIN DESCRIPTION:
elmc690
END DESCRIPTION:
XS GIS Cut Line= 3
      1497496.54      6768333.46      1497461.39      6768179.80
      1497410.62      6768057.44
#Sta/Elev= 30
  4844.6 2365.71  4850.2 2364.00  4860.5 2363.17  4865.2 2362.21  4869.8 2361.27
  4874.9 2362.05  4881.0 2358.93  4911.8 2348.64  4917.8 2344.75  4923.0 2344.54
  4932.3 2341.57  4942.5 2338.79  4960.8 2334.13  4965.9 2333.47  4981.6 2329.31
  4981.8 2328.81  4985.3 2328.81  4985.6 2329.31  5015.0 2330.40  5031.6 2331.65
  5037.0 2332.37  5047.5 2332.84  5060.9 2336.31  5079.3 2341.99  5084.8 2343.36
  5090.8 2346.28  5101.6 2348.54  5108.6 2351.24  5131.7 2356.98  5134.7 2356.98
#Mann=4,-1,0
  4844.6    0.07       0  4865.2    0.16       0  4981.6    0.07       0
  4985.6    0.16       0
Bank Sta=4981.6,4985.6
Exp/Cntr=0.3,0.1

Type RM Length L Ch R = 1,1037,118,118,118
BEGIN DESCRIPTION:
elmc395
END DESCRIPTION:
XS GIS Cut Line= 3
      1497505.00      6768338.00      1497511.04      6768140.49
      1497505.00      6768037.97
#Sta/Elev= 30
  4802.4 2365.44  4804.9 2365.44  4812.4 2363.95  4821.5 2362.98  4832.4 2360.93
  4842.4 2358.52  4852.4 2355.35  4862.4 2352.60  4892.4 2341.71  4902.4 2338.57
  4912.5 2336.31  4932.5 2332.95  4942.5 2331.73  4952.5 2330.89  4961.8 2328.84
  4966.8 2331.22  4972.5 2329.53  4980.5 2327.68  4980.7 2327.18  4984.2 2327.18
  4984.5 2327.68  5003.8 2328.19  5012.5 2329.97  5032.5 2332.11  5042.6 2334.74
  5062.6 2341.00  5082.6 2347.76  5092.7 2351.49  5100.2 2354.76  5102.7 2354.76
#Mann=4,-1,0
  4802.4    0.07       0  4821.5    0.16       0  4980.5    0.07       0
  4984.5    0.16       0
Bank Sta=4980.5,4984.5
Exp/Cntr=0.3,0.1

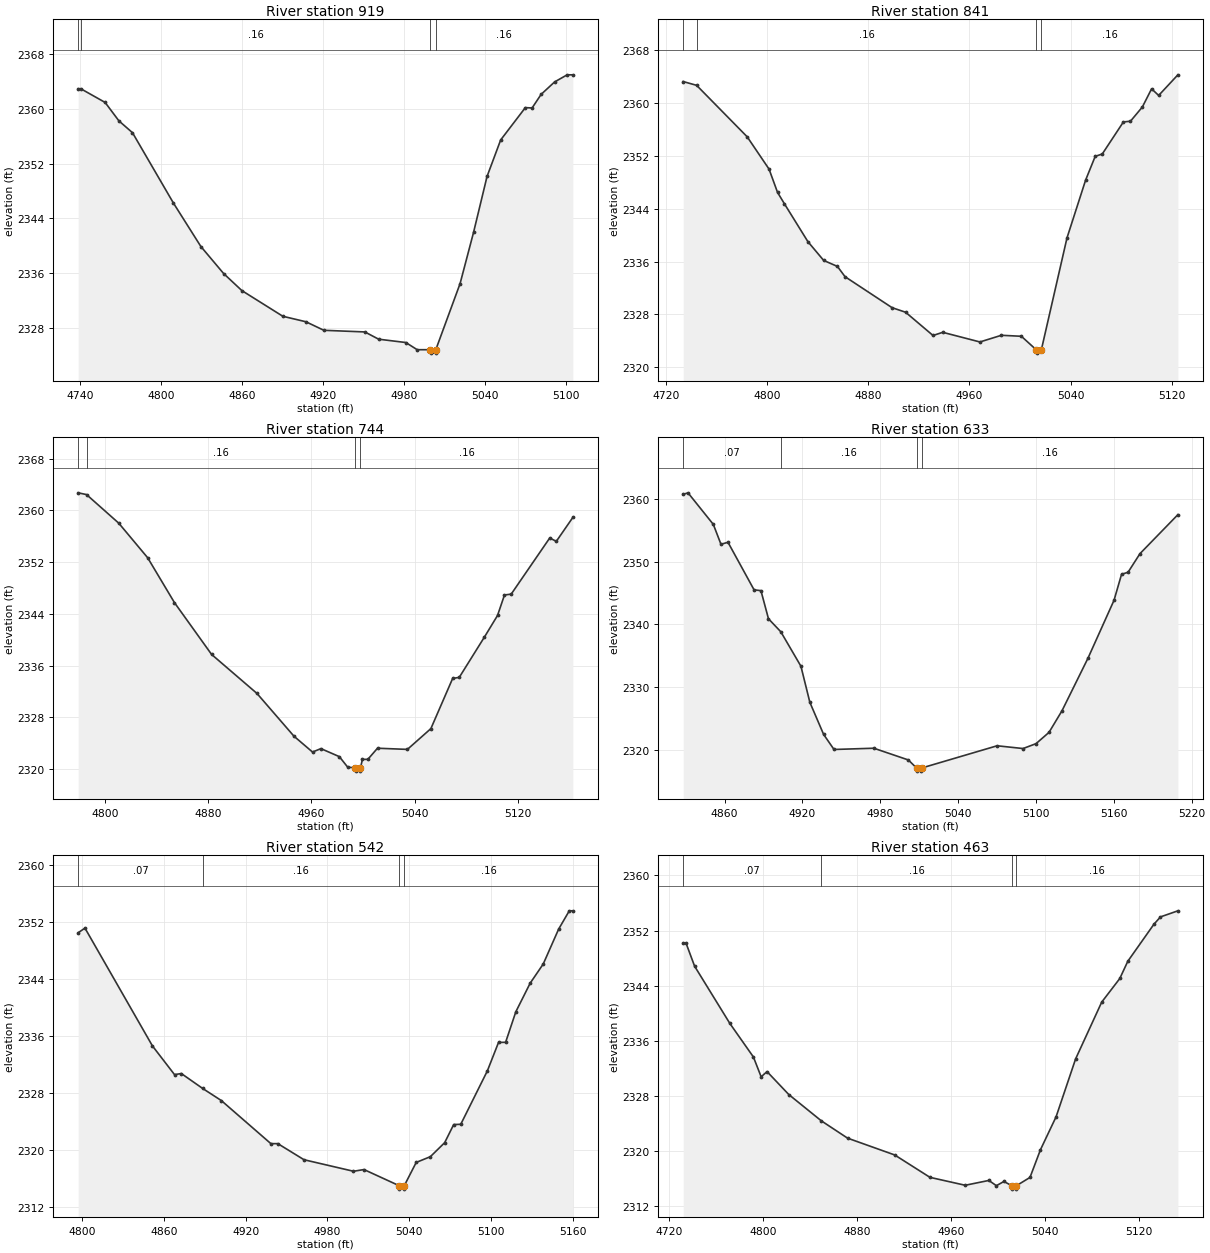
Type RM Length L Ch R = 1,919,78,78,78
BEGIN DESCRIPTION:
elmc688
END DESCRIPTION:
XS GIS Cut Line= 3
      1497572.06      6768347.76      1497613.73      6768096.47
      1497608.52      6767984.52
#Sta/Elev= 30
  4738.4 2362.97  4740.4 2362.97  4758.4 2360.97  4768.6 2358.28  4778.7 2356.54
  4809.1 2346.23  4829.4 2339.89  4846.3 2335.93  4859.8 2333.44  4890.2 2329.68
  4907.3 2328.88  4920.6 2327.63  4951.0 2327.39  4961.2 2326.33  4981.4 2325.84
  4989.8 2324.79  4999.6 2324.79  4999.9 2324.29  5003.4 2324.29  5003.6 2324.79
  5021.6 2334.46  5031.6 2341.96  5041.6 2350.14  5051.7 2355.48  5070.0 2360.21
  5075.0 2360.16  5081.7 2362.15  5091.7 2363.97  5101.0 2365.01  5105.2 2365.01
#Mann=4,-1,0
  4738.4    0.07       0  4740.4    0.16       0  4999.6    0.07       0
  5003.6    0.16       0
Bank Sta=4999.6,5003.6
Exp/Cntr=0.3,0.1

Type RM Length L Ch R = 1,841,97,97,97
BEGIN DESCRIPTION:
elmc687
END DESCRIPTION:
XS GIS Cut Line= 3
      1497581.17      6768360.82      1497682.74      6768113.40
      1497738.64      6768002.89
#Sta/Elev= 30
  4733.6 2363.25  4744.2 2362.68  4784.2 2354.89  4801.5 2350.00  4808.2 2346.48
  4813.6 2344.77  4832.2 2339.03  4844.7 2336.18  4855.6 2335.27  4861.6 2333.72
  4898.8 2329.03  4909.5 2328.34  4931.2 2324.82  4938.9 2325.30  4968.3 2323.84
  4985.3 2324.85  5001.1 2324.70  5012.9 2322.65  5013.2 2322.15  5016.9 2322.65
  5037.2 2339.60  5051.9 2348.33  5059.5 2351.93  5065.1 2352.29  5081.8 2357.14
  5087.4 2357.25  5096.8 2359.40  5104.1 2362.15  5109.7 2361.15  5124.9 2364.27
#Mann=4,-1,0
  4733.6    0.07       0  4744.2    0.16       0  5012.9    0.07       0
  5016.9    0.16       0
Bank Sta=5012.9,5016.9
Exp/Cntr=0.3,0.1

Type RM Length L Ch R = 1,744,111,111,111
BEGIN DESCRIPTION:
elmc686
END DESCRIPTION:
XS GIS Cut Line= 3
      1497592.89      6768360.80      1497732.22      6768187.62
      1497773.49      6768031.55
#Sta/Elev= 30
  4779.1 2362.73  4785.6 2362.46  4810.6 2358.04  4833.0 2352.70  4853.8 2345.76
  4882.6 2337.75  4917.8 2331.72  4946.5 2325.11  4960.9 2322.66  4967.4 2323.19
  4981.7 2321.95  4988.2 2320.32  4994.1 2320.21  4994.4 2319.71  4997.9 2319.71
  4998.1 2320.21  4999.6 2321.53  5003.8 2321.53  5011.3 2323.25  5034.5 2323.07
  5052.7 2326.28  5069.6 2334.04  5074.7 2334.20  5094.1 2340.39  5104.4 2343.77
  5109.8 2346.94  5115.0 2347.07  5144.9 2355.75  5150.0 2355.23  5162.8 2358.92
#Mann=4,-1,0
  4779.1    0.07       0  4785.6    0.16       0  4994.1    0.07       0
  4998.1    0.16       0
Bank Sta=4994.1,4998.1
Exp/Cntr=0.3,0.1

Type RM Length L Ch R = 1,633,91,91,91
BEGIN DESCRIPTION:
elmc685
END DESCRIPTION:
XS GIS Cut Line= 3
      1497769.98      6768399.86      1497827.27      6768239.70
      1497818.16      6768028.80
#Sta/Elev= 30
  4828.1 2360.72  4831.8 2360.96  4851.3 2355.93  4857.2 2352.76  4862.6 2353.08
  4882.7 2345.50  4888.0 2345.37  4893.8 2340.89  4903.3 2338.82  4918.8 2333.33
  4925.7 2327.57  4936.3 2322.46  4944.3 2320.06  4975.0 2320.26  5001.6 2318.39
  5007.9 2317.11  5008.2 2316.61  5011.7 2316.61  5011.9 2317.11  5070.0 2320.65
  5090.0 2320.21  5100.0 2320.99  5110.0 2322.79  5120.0 2326.23  5140.0 2334.60
  5160.1 2343.84  5165.9 2347.98  5170.9 2348.30  5180.1 2351.27  5209.3 2357.48
#Mann=4,-1,0
  4828.1    0.07       0  4903.3    0.16       0  5007.9    0.07       0
  5011.9    0.16       0
Bank Sta=5007.9,5011.9
Exp/Cntr=0.3,0.1

Type RM Length L Ch R = 1,542,79,79,79
BEGIN DESCRIPTION:
elmc394
END DESCRIPTION:
XS GIS Cut Line= 3
      1497930.13      6768391.99      1497901.46      6768191.13
      1497855.01      6768038.02
#Sta/Elev= 30
  4797.1 2350.52  4802.1 2351.17  4851.6 2334.62  4867.8 2330.59  4872.8 2330.74
  4888.4 2328.65  4902.1 2326.95  4938.5 2320.89  4943.6 2320.89  4962.8 2318.63
  4999.1 2317.01  5006.8 2317.25  5032.4 2315.00  5032.7 2314.50  5036.2 2314.50
  5036.4 2315.00  5045.1 2318.25  5055.5 2319.06  5066.0 2321.03  5072.6 2323.57
  5077.8 2323.61  5097.3 2331.11  5105.5 2335.11  5110.7 2335.13  5118.2 2339.42
  5128.7 2343.43  5138.3 2346.13  5149.6 2351.03  5157.4 2353.60  5160.0 2353.60
#Mann=4,-1,0
  4797.1    0.07       0  4888.4    0.16       0  5032.4    0.07       0
  5036.4    0.16       0
Bank Sta=5032.4,5036.4
Exp/Cntr=0.3,0.1

Type RM Length L Ch R = 1,463,87,87,87
BEGIN DESCRIPTION:
elmc707
END DESCRIPTION:
XS GIS Cut Line= 3
      1497973.11      6768407.69      1497960.86      6768140.07
      1497891.07      6768004.02
#Sta/Elev= 30
  4732.1 2350.17  4734.5 2350.17  4741.8 2346.82  4771.8 2338.51  4791.8 2333.65
  4798.4 2330.77  4803.4 2331.53  4821.9 2328.20  4849.6 2324.38  4871.9 2321.87
  4912.0 2319.43  4942.0 2316.18  4972.0 2315.03  4992.1 2315.73  4998.5 2314.97
  5004.9 2315.58  5011.6 2314.97  5011.8 2314.47  5015.3 2314.47  5015.6 2314.97
  5027.1 2316.17  5036.0 2320.19  5049.3 2324.97  5065.9 2333.37  5088.1 2341.61
  5103.5 2345.04  5110.3 2347.54  5132.5 2352.91  5138.1 2353.98  5152.9 2354.86
#Mann=4,-1,0
  4732.1    0.07       0  4849.6    0.16       0  5011.6    0.07       0
  5015.6    0.16       0
Bank Sta=5011.6,5015.6
Exp/Cntr=0.3,0.1

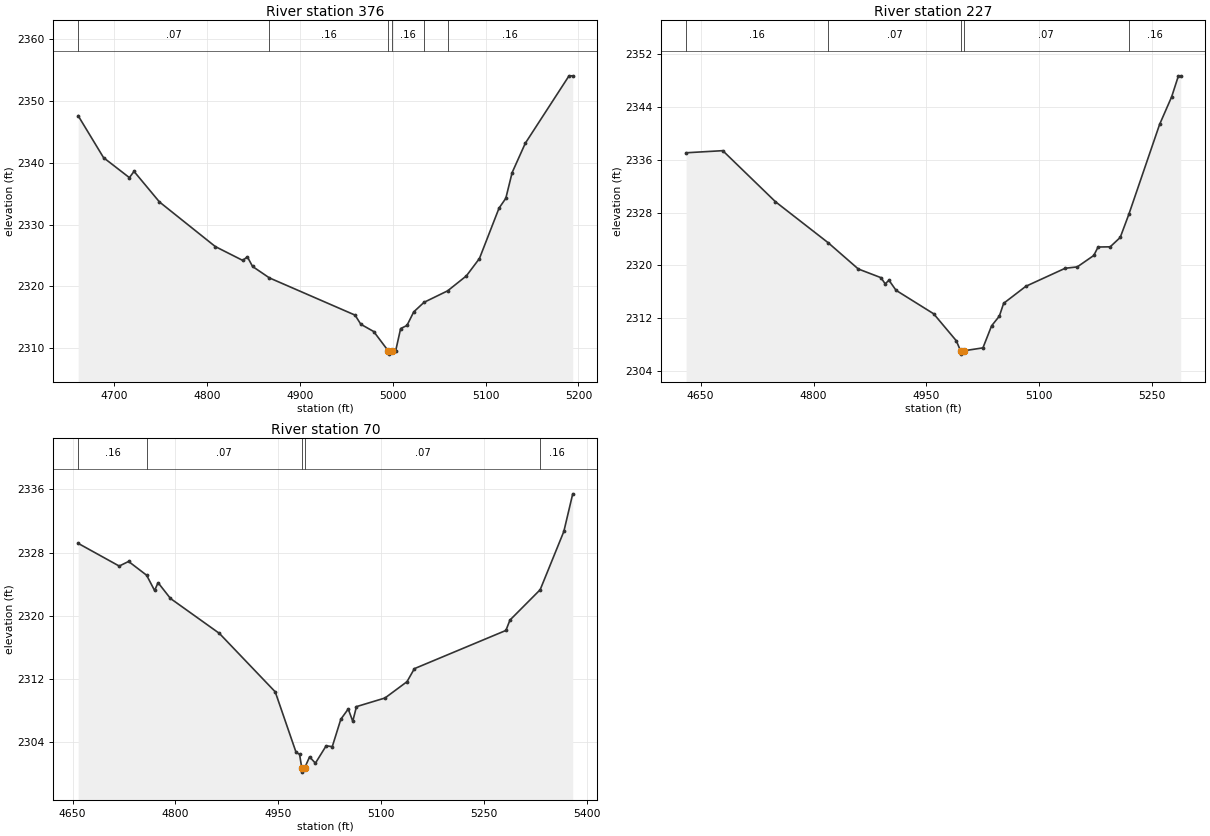
Type RM Length L Ch R = 1,376,149,149,149
BEGIN DESCRIPTION:
elmc706
END DESCRIPTION:
XS GIS Cut Line= 3
      1498074.66      6768475.33      1498047.32      6768137.53
      1497914.54      6767996.24
#Sta/Elev= 30
  4661.1 2347.64  4688.5 2340.84  4716.3 2337.61  4721.3 2338.62  4748.7 2333.67
  4808.9 2326.44  4838.4 2324.20  4843.4 2324.78  4849.0 2323.22  4867.1 2321.37
  4959.4 2315.34  4965.6 2313.86  4979.5 2312.68  4995.3 2309.52  4995.5 2309.02
  4999.3 2309.52  5003.1 2309.52  5008.5 2313.16  5015.3 2313.66  5022.6 2315.86
  5033.7 2317.41  5059.1 2319.27  5079.3 2321.69  5093.4 2324.51  5114.5 2332.67
  5121.8 2334.26  5128.6 2338.42  5142.8 2343.18  5189.9 2354.10  5193.9 2354.10
#Mann=6,-1,0
  4661.1    0.07       0  4867.1    0.16       0  4995.3    0.07       0
  4999.3    0.16       0  5033.7    0.07       0  5059.1    0.16       0
Bank Sta=4995.3,4999.3
Exp/Cntr=0.3,0.1

Type RM Length L Ch R = 1,227,157,157,157
BEGIN DESCRIPTION:
elmc705
END DESCRIPTION:
XS GIS Cut Line= 3
      1498207.48      6768506.64      1498197.06      6768137.59
      1497944.45      6768000.11
#Sta/Elev= 30
  4630.8 2337.07  4679.5 2337.39  4749.5 2329.65  4819.8 2323.41  4859.5 2319.46
  4889.5 2318.15  4895.2 2317.21  4900.2 2317.76  4909.6 2316.23  4959.6 2312.67
  4989.6 2308.59  4995.3 2307.06  4995.5 2306.56  4999.3 2307.06  5025.0 2307.51
  5036.5 2310.85  5046.8 2312.32  5052.5 2314.26  5082.0 2316.84  5134.2 2319.57
  5150.3 2319.78  5172.2 2321.51  5177.9 2322.79  5194.0 2322.82  5207.3 2324.24
  5218.8 2327.76  5259.6 2341.37  5275.6 2345.55  5284.6 2348.73  5287.6 2348.73
#Mann=5,-1,0
  4630.8    0.16       0  4819.8    0.07       0  4995.3    0.07       0
  4999.3    0.07       0  5218.8    0.16       0
Bank Sta=4995.3,4999.3
Exp/Cntr=0.3,0.1

Type RM Length L Ch R = 1,70,0,0,0
BEGIN DESCRIPTION:
elmc704
END DESCRIPTION:
XS GIS Cut Line= 3
      1498288.20      6768470.19      1498353.64      6768134.71
      1497999.54      6767997.66
#Sta/Elev= 30
  4658.2 2329.16  4718.1 2326.29  4731.8 2326.87  4758.1 2325.13  4769.7 2323.20
  4774.8 2324.19  4792.9 2322.19  4864.2 2317.78  4945.7 2310.39  4976.1 2302.74
  4981.2 2302.49  4984.5 2300.74  4984.7 2300.24  4988.5 2300.74  4995.8 2302.17
  5004.3 2301.37  5020.0 2303.57  5028.9 2303.46  5041.4 2306.93  5052.2 2308.22
  5058.8 2306.67  5064.2 2308.52  5105.8 2309.61  5137.9 2311.67  5148.7 2313.32
  5282.2 2318.15  5288.1 2319.46  5332.2 2323.30  5366.7 2330.66  5379.7 2335.42
#Mann=5,-1,0
  4658.2    0.16       0  4758.1    0.07       0  4984.5    0.07       0
  4988.5    0.07       0  5332.2    0.16       0
Bank Sta=4984.5,4988.5
Exp/Cntr=0.3,0.1

Chan Stop Cuts=-1