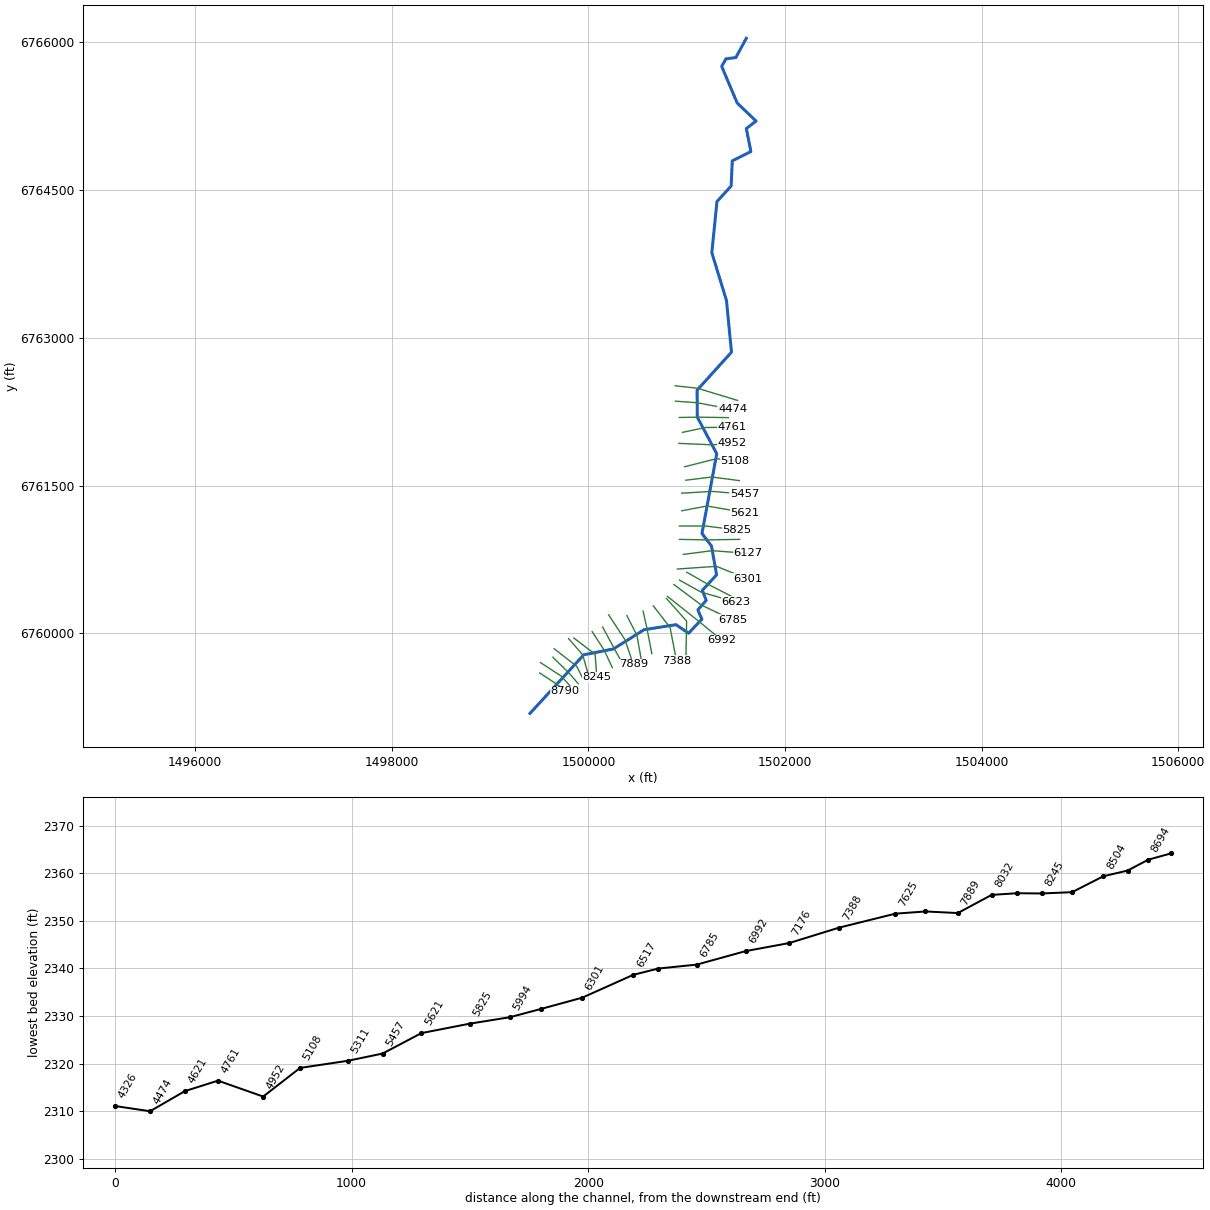
--- Elm 35.prj (project) ---

Proj Title=Elm 35 Base Level Engineering
Current Plan=p01
Default Exp/Contr=0.3,0.1
English Units
Geom File=g01
Flow File=f01
Plan File=p01
BEGIN DESCRIPTION:
Elm 35
END DESCRIPTION:

--- Elm 35.p01 (plan) ---

Plan Title=Multiple Run
Short Identifier=Multiple
Geom File=g01
Flow File=f01
Subcritical Flow
K Sum by GR= 0
Std Step Tol= 0.01
Critical Tol= 0.01
Num of Std Step Trials= 20
Max Error Tol= 0.3
Flow Tol Ratio= 0.001
Split Flow NTrial= 30
Split Flow Tol= 0.02
Split Flow Ratio= 0.02
Log Output Level= 0
Friction Slope Method= 1
Unsteady Friction Slope Method= 2
Unsteady Bridges Friction Slope Method= 1
Parabolic Critical Depth
Global Vel Dist=  1 , 1 , 1
Global Log Level= 0
CheckData=True
Encroach Param= -1, 0, 0, 0
BEGIN DESCRIPTION:
Multiple Run
END DESCRIPTION:

--- Elm 35.f01 (steady flow) ---

Flow Title=Multiple
Number of Profiles=7
Profile Names=10-year,25-year,50-year,1pct_min,100-year,1pct_plu,500-year
River Rch & RM= Elm 35,Reach-1,8790
     341     485     606     470     753    1040    1180
Boundary for River Rch & Prof#=Elm 35,Reach-1,1
Up Type=0
Dn Type=3
Dn Slope=0.005
Boundary for River Rch & Prof#=Elm 35,Reach-1,2
Up Type=0
Dn Type=3
Dn Slope=0.005
Boundary for River Rch & Prof#=Elm 35,Reach-1,3
Up Type=0
Dn Type=3
Dn Slope=0.005
Boundary for River Rch & Prof#=Elm 35,Reach-1,4
Up Type=0
Dn Type=3
Dn Slope=0.005
Boundary for River Rch & Prof#=Elm 35,Reach-1,5
Up Type=0
Dn Type=3
Dn Slope=0.005
Boundary for River Rch & Prof#=Elm 35,Reach-1,6
Up Type=0
Dn Type=3
Dn Slope=0.005
Boundary for River Rch & Prof#=Elm 35,Reach-1,7
Up Type=0
Dn Type=3
Dn Slope=0.005

--- Elm 35.g01 (geometry) ---

Geom Title=Existing Conditions

River Reach=Elm 35,Reach-1
Reach XY= 30
      1499405.00      6759188.00      1499952.30      6759782.64
      1500253.50      6759841.62      1500565.44      6760036.94
      1500889.66      6760088.04      1501018.34      6760001.41
      1501153.34      6760144.05      1501112.37      6760238.09
      1501197.15      6760334.59      1501158.16      6760436.35
      1501303.04      6760593.89      1501251.44      6760886.53
      1501154.51      6761012.96      1501304.62      6761822.73
      1501107.06      6762193.86      1501104.96      6762468.02
      1501454.64      6762853.16      1501403.78      6763377.50
      1501254.77      6763863.07      1501307.06      6764382.15
      1501451.46      6764539.46      1501462.68      6764794.52
      1501651.97      6764889.39      1501605.66      6765122.15
      1501704.51      6765198.54      1501512.86      6765381.81
      1501355.00      6765753.48      1501398.50      6765830.24
      1501499.55      6765843.25      1501605.00      6766038.00

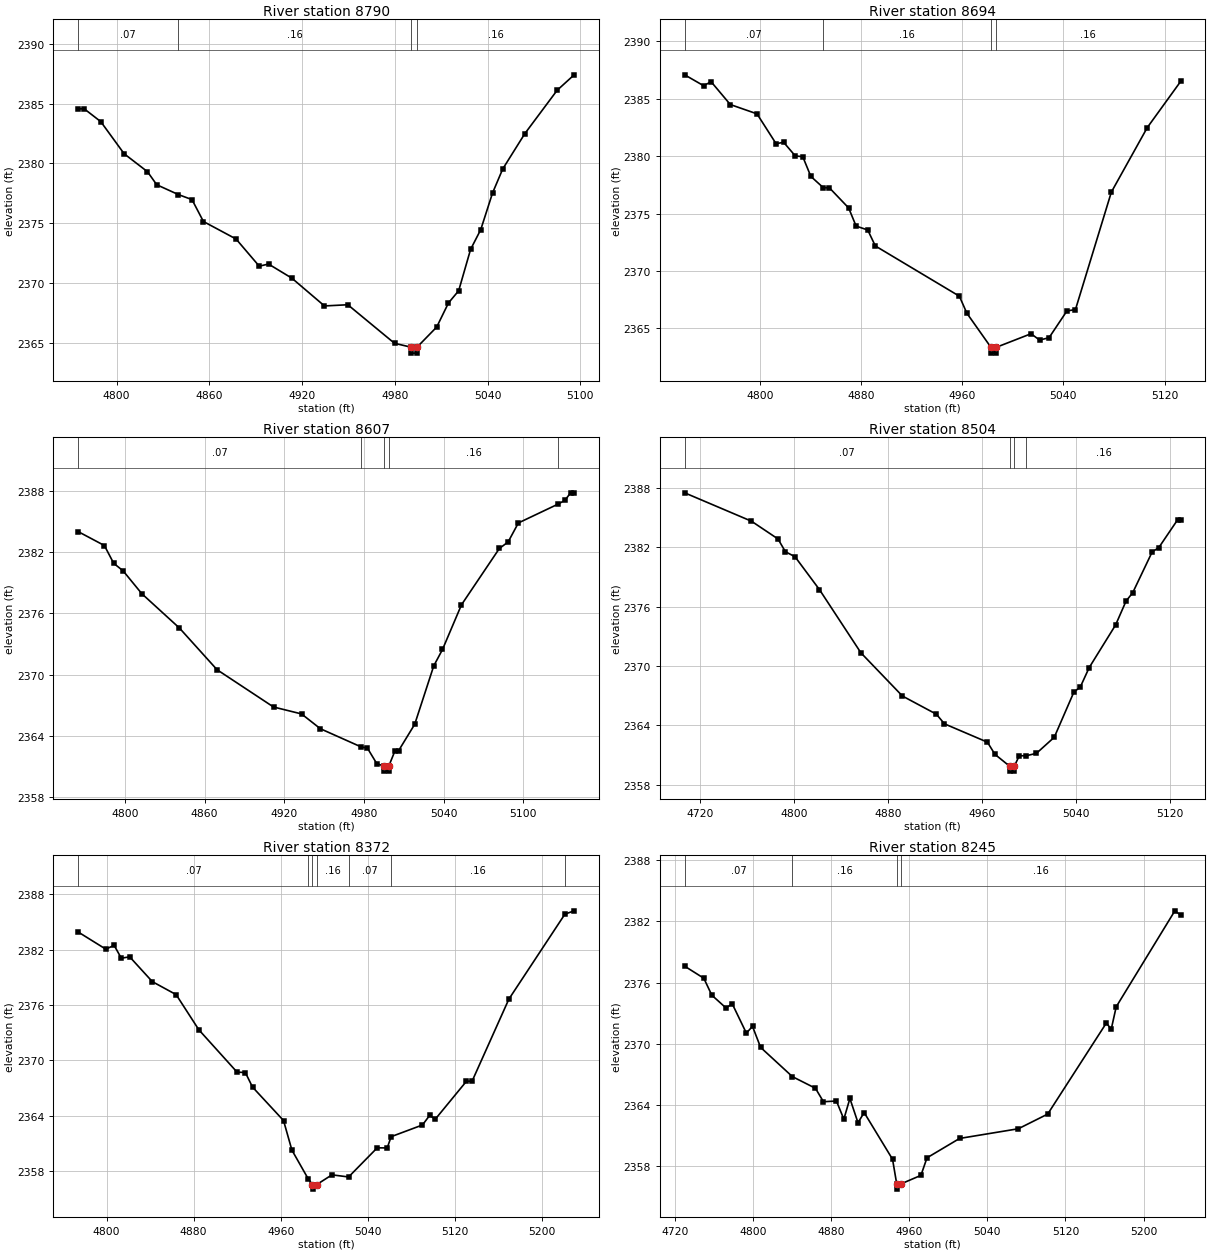
Type RM Length L Ch R = 1,8790,96,96,96
BEGIN DESCRIPTION:
elmc372
END DESCRIPTION:
XS GIS Cut Line= 3
      1499503.47      6759598.22      1499691.36      6759474.80
      1499763.86      6759411.87
#Sta/Elev= 30
  4775.2 2384.56  4779.1 2384.56  4789.8 2383.49  4804.9 2380.81  4820.0 2379.31
  4826.0 2378.22  4840.0 2377.40  4848.8 2376.98  4856.2 2375.15  4877.3 2373.69
  4892.3 2371.42  4898.3 2371.60  4913.4 2370.42  4934.5 2368.10  4949.6 2368.20
  4979.8 2364.98  4990.4 2364.66  4990.6 2364.16  4994.1 2364.16  4994.4 2364.66
  5007.1 2366.34  5014.7 2368.35  5021.3 2369.37  5029.0 2372.82  5035.6 2374.48
  5043.2 2377.53  5049.8 2379.54  5064.1 2382.49  5085.0 2386.11  5096.0 2387.40
#Mann=4,-1,0
  4775.2    0.07       0  4840.0    0.16       0  4990.4    0.07       0
  4994.4    0.16       0
Bank Sta=4990.4,4994.4
Exp/Cntr=0.3,0.1

Type RM Length L Ch R = 1,8694,87,87,87
BEGIN DESCRIPTION:
elmc759
END DESCRIPTION:
XS GIS Cut Line= 3
      1499511.30      6759703.67      1499723.54      6759565.65
      1499816.61      6759462.24
#Sta/Elev= 30
  4740.4 2387.09  4755.4 2386.14  4761.3 2386.49  4776.5 2384.50  4797.6 2383.69
  4812.7 2381.09  4818.7 2381.21  4827.9 2380.02  4833.8 2379.96  4840.2 2378.24
  4850.0 2377.26  4854.9 2377.24  4870.1 2375.49  4876.0 2373.91  4885.2 2373.57
  4891.2 2372.18  4957.7 2367.80  4963.6 2366.32  4982.7 2363.34  4983.0 2362.84
  4986.5 2362.84  4986.7 2363.34  5014.4 2364.53  5021.1 2363.98  5028.6 2364.18
  5042.8 2366.52  5049.5 2366.63  5077.9 2376.87  5106.3 2382.49  5132.7 2386.51
#Mann=4,-1,0
  4740.4    0.07       0  4850.0    0.16       0  4982.7    0.07       0
  4986.7    0.16       0
Bank Sta=4982.7,4986.7
Exp/Cntr=0.3,0.1

Type RM Length L Ch R = 1,8607,103,103,103
BEGIN DESCRIPTION:
elmc758
END DESCRIPTION:
XS GIS Cut Line= 3
      1499637.59      6759758.37      1499809.48      6759589.09
      1499895.41      6759488.83
#Sta/Elev= 30
  4764.9 2384.01  4784.6 2382.65  4791.6 2380.91  4798.7 2380.17  4812.8 2377.93
  4841.1 2374.57  4869.4 2370.49  4911.9 2366.84  4933.0 2366.16  4947.2 2364.71
  4977.7 2362.94  4982.6 2362.81  4989.6 2361.30  4994.7 2361.06  4995.0 2360.56
  4998.5 2360.56  4998.7 2361.06  5003.4 2362.57  5006.1 2362.57  5018.2 2365.15
  5032.5 2370.86  5039.1 2372.47  5053.4 2376.85  5081.9 2382.36  5088.5 2383.00
  5096.2 2384.86  5126.0 2386.70  5131.3 2387.08  5135.5 2387.81  5138.2 2387.81
#Mann=5,-1,0
  4764.9    0.07       0  4977.7    0.16       0  4994.7    0.07       0
  4998.7    0.16       0  5126.0    0.07       0
Bank Sta=4994.7,4998.7
Exp/Cntr=0.3,0.1

Type RM Length L Ch R = 1,8504,132,132,132
BEGIN DESCRIPTION:
elmc757
END DESCRIPTION:
XS GIS Cut Line= 3
      1499650.61      6759844.31      1499879.79      6759665.91
      1499939.67      6759548.76
#Sta/Elev= 30
  4707.1 2387.53  4763.9 2384.66  4786.5 2382.86  4792.8 2381.57  4801.0 2381.06
  4821.8 2377.73  4857.1 2371.33  4892.4 2366.96  4921.3 2365.12  4928.1 2364.15
  4964.7 2362.29  4971.1 2361.06  4983.6 2359.86  4983.8 2359.36  4987.3 2359.36
  4987.6 2359.86  4991.8 2360.91  4997.8 2360.92  5006.4 2361.16  5021.6 2362.79
  5038.2 2367.34  5043.8 2367.89  5051.3 2369.84  5073.8 2374.16  5082.7 2376.58
  5088.3 2377.41  5104.9 2381.55  5110.5 2381.98  5126.7 2384.83  5129.1 2384.83
#Mann=4,-1,0
  4707.1    0.07       0  4983.6    0.07       0  4987.6    0.07       0
  4997.8    0.16       0
Bank Sta=4983.6,4987.6
Exp/Cntr=0.3,0.1

Type RM Length L Ch R = 1,8372,127,127,127
BEGIN DESCRIPTION:
elmc755
END DESCRIPTION:
XS GIS Cut Line= 3
      1499797.74      6759947.19      1499940.99      6759781.80
      1500006.10      6759553.92
#Sta/Elev= 30
  4773.9 2383.91  4799.3 2382.05  4806.9 2382.47  4813.5 2381.07  4821.2 2381.22
  4842.0 2378.53  4863.9 2377.12  4884.8 2373.30  4919.9 2368.71  4927.5 2368.67
  4934.1 2367.09  4962.6 2363.46  4970.3 2360.25  4985.5 2357.09  4989.2 2356.52
  4989.4 2356.02  4993.2 2356.52  5007.1 2357.57  5022.4 2357.34  5048.7 2360.50
  5057.9 2360.49  5061.5 2361.71  5090.3 2362.98  5096.9 2364.02  5102.1 2363.61
  5130.7 2367.72  5135.9 2367.73  5169.7 2376.63  5221.2 2385.85  5229.7 2386.21
#Mann=7,-1,0
  4773.9    0.07       0  4985.5    0.16       0  4989.2    0.07       0
  4993.2    0.16       0  5022.4    0.07       0  5061.5    0.16       0
  5221.2    0.07       0
Bank Sta=4989.2,4993.2
Exp/Cntr=0.3,0.1

Type RM Length L Ch R = 1,8245,106,106,106
BEGIN DESCRIPTION:
elmc756
END DESCRIPTION:
XS GIS Cut Line= 3
      1499851.15      6759952.37      1500067.29      6759788.31
      1500085.45      6759552.15
#Sta/Elev= 30
  4729.8 2377.61  4749.4 2376.43  4757.6 2374.77  4772.2 2373.51  4778.5 2373.93
  4793.0 2371.05  4799.3 2371.71  4807.6 2369.65  4840.2 2366.78  4863.8 2365.64
  4872.0 2364.32  4885.3 2364.39  4892.9 2362.61  4899.1 2364.64  4907.4 2362.26
  4913.7 2363.26  4942.8 2358.68  4947.1 2356.25  4947.3 2355.75  4951.1 2356.25
  4971.9 2357.10  4978.1 2358.82  5011.5 2360.72  5071.7 2361.67  5101.8 2363.11
  5161.9 2372.04  5166.9 2371.43  5172.0 2373.63  5232.1 2383.04  5238.0 2382.63
#Mann=4,-1,0
  4729.8    0.07       0  4840.2    0.16       0  4947.1    0.07       0
  4951.1    0.16       0
Bank Sta=4947.1,4951.1
Exp/Cntr=0.3,0.1

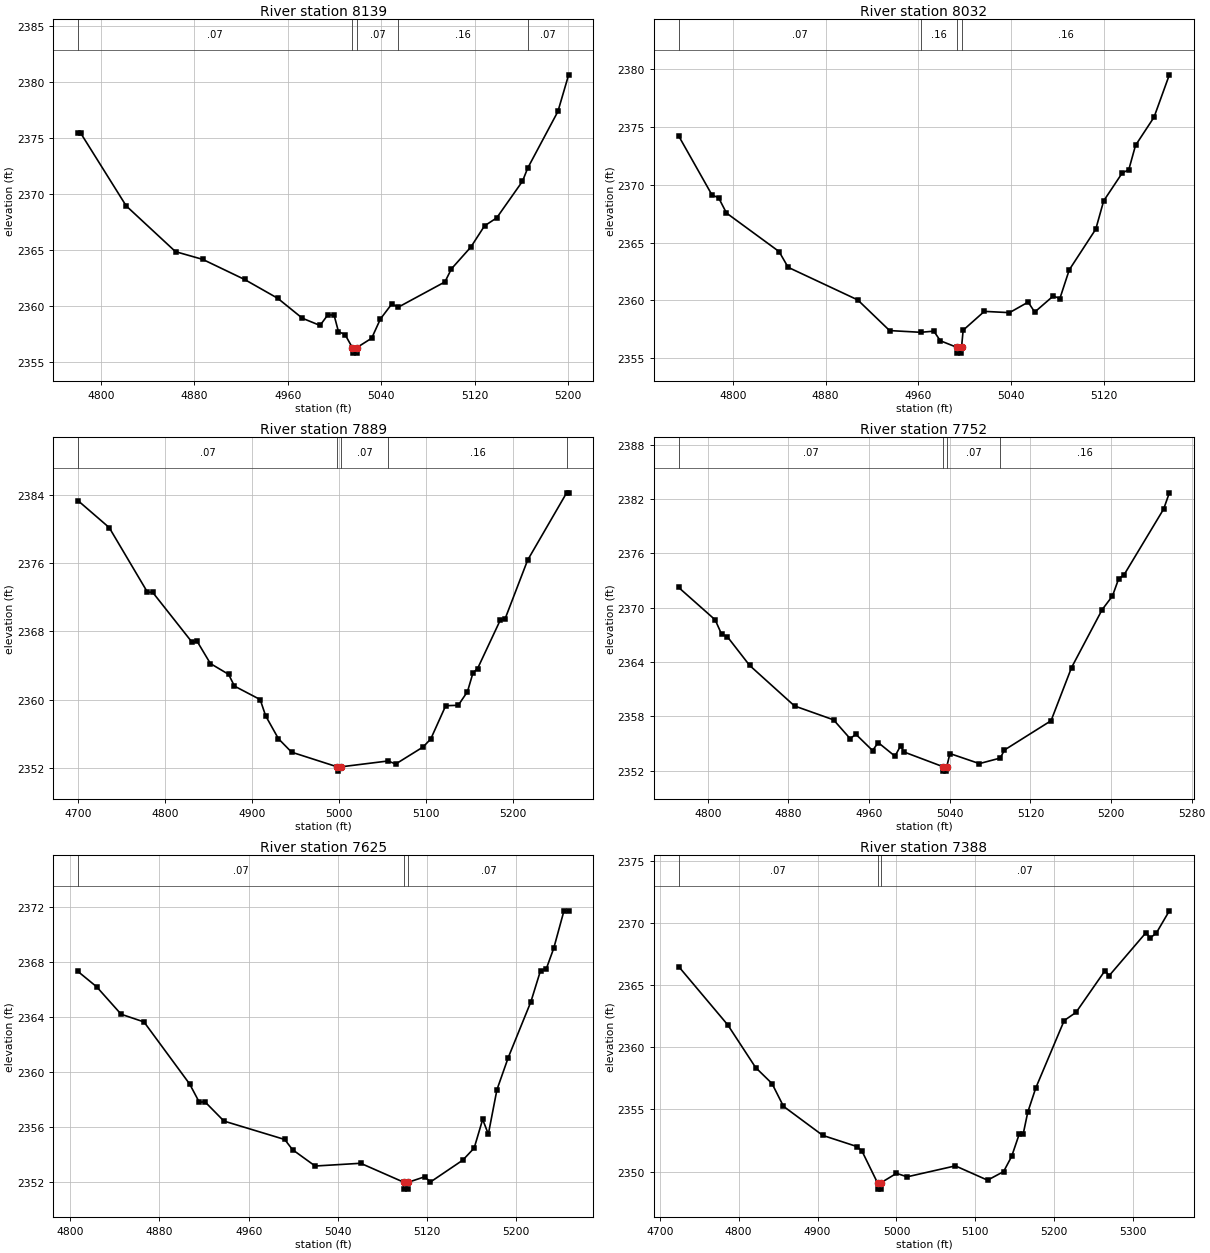
Type RM Length L Ch R = 1,8139,107,107,107
BEGIN DESCRIPTION:
elmc753
END DESCRIPTION:
XS GIS Cut Line= 3
      1500037.35      6760017.46      1500157.13      6759833.88
      1500242.76      6759652.25
#Sta/Elev= 30
  4780.5 2375.41  4782.9 2375.41  4821.8 2368.93  4864.0 2364.85  4887.3 2364.16
  4923.1 2362.37  4951.5 2360.69  4972.6 2358.91  4987.7 2358.27  4994.3 2359.20
  4999.7 2359.20  5003.5 2357.71  5009.1 2357.46  5015.3 2356.30  5015.5 2355.80
  5019.0 2355.80  5019.3 2356.30  5031.9 2357.13  5039.4 2358.85  5049.1 2360.18
  5054.7 2359.90  5094.6 2362.15  5100.2 2363.32  5116.8 2365.26  5128.5 2367.15
  5138.9 2367.86  5161.0 2371.13  5165.4 2372.29  5191.3 2377.35  5200.5 2380.62
#Mann=5,-1,0
  4780.5    0.07       0  5015.3    0.07       0  5019.3    0.07       0
  5054.7    0.16       0  5165.4    0.07       0
Bank Sta=5015.3,5019.3
Exp/Cntr=0.3,0.1

Type RM Length L Ch R = 1,8032,143,143,143
BEGIN DESCRIPTION:
elmc754
END DESCRIPTION:
XS GIS Cut Line= 3
      1500144.13      6760064.32      1500261.30      6759846.90
      1500346.96      6759692.45
#Sta/Elev= 30
  4753.2 2374.23  4782.0 2369.12  4787.7 2368.88  4794.5 2367.56  4839.9 2364.23
  4847.7 2362.87  4907.8 2360.05  4935.3 2357.40  4962.2 2357.25  4973.5 2357.35
  4979.1 2356.52  4993.4 2355.95  4993.6 2355.45  4997.1 2355.45  4997.4 2355.95
  4998.8 2357.43  5017.1 2359.06  5038.8 2358.95  5054.9 2359.86  5060.6 2359.00
  5076.6 2360.39  5082.3 2360.17  5090.4 2362.65  5113.3 2366.17  5120.1 2368.61
  5136.1 2371.02  5141.8 2371.31  5147.6 2373.41  5163.6 2375.85  5176.8 2379.51
#Mann=4,-1,0
  4753.2    0.07       0  4962.2    0.16       0  4993.4    0.07       0
  4997.4    0.16       0
Bank Sta=4993.4,4997.4
Exp/Cntr=0.3,0.1

Type RM Length L Ch R = 1,7889,137,137,137
BEGIN DESCRIPTION:
elmc371
END DESCRIPTION:
XS GIS Cut Line= 3
      1500205.00      6760187.99      1500370.22      6759937.47
      1500455.01      6759687.98
#Sta/Elev= 30
  4699.9 2383.32  4735.8 2380.16  4779.7 2372.60  4785.7 2372.58  4830.9 2366.74
  4836.9 2366.82  4852.0 2364.24  4873.0 2362.97  4879.6 2361.60  4909.2 2360.02
  4915.5 2358.11  4930.2 2355.43  4945.3 2353.86  4997.8 2352.14  4998.1 2351.64
  5001.8 2352.14  5056.2 2352.83  5064.8 2352.47  5096.2 2354.46  5105.1 2355.40
  5122.3 2359.30  5136.7 2359.35  5147.3 2360.95  5153.6 2363.14  5158.9 2363.65
  5185.0 2369.33  5190.3 2369.42  5216.4 2376.35  5261.2 2384.23  5263.5 2384.23
#Mann=5,-1,0
  4699.9    0.07       0  4997.8    0.07       0  5001.8    0.07       0
  5056.2    0.16       0  5261.2    0.07       0
Bank Sta=4997.8,5001.8
Exp/Cntr=0.3,0.1

Type RM Length L Ch R = 1,7752,127,127,127
BEGIN DESCRIPTION:
elmc752
END DESCRIPTION:
XS GIS Cut Line= 3
      1500390.22      6760180.22      1500493.07      6759979.72
      1500538.55      6759722.45
#Sta/Elev= 30
  4771.2 2372.23  4807.4 2368.66  4813.8 2367.07  4819.4 2366.81  4841.6 2363.63
  4886.1 2359.16  4924.8 2357.63  4941.3 2355.55  4946.9 2356.04  4963.5 2354.24
  4969.1 2355.12  4985.7 2353.62  4991.3 2354.76  4994.7 2354.08  5033.1 2352.47
  5033.3 2351.97  5036.8 2351.97  5037.1 2352.47  5040.2 2353.91  5069.4 2352.80
  5090.1 2353.41  5094.3 2354.30  5140.5 2357.53  5160.8 2363.39  5191.2 2369.79
  5201.4 2371.29  5207.6 2373.21  5212.7 2373.59  5252.2 2380.89  5257.8 2382.67
#Mann=4,-1,0
  4771.2    0.07       0  5033.1    0.07       0  5037.1    0.07       0
  5090.1    0.16       0
Bank Sta=5033.1,5037.1
Exp/Cntr=0.3,0.1

Type RM Length L Ch R = 1,7625,237,237,237
BEGIN DESCRIPTION:
elmc751
END DESCRIPTION:
XS GIS Cut Line= 3
      1500555.58      6760225.78      1500595.93      6760044.82
      1500644.11      6759794.83
#Sta/Elev= 30
  4806.9 2367.34  4823.6 2366.23  4845.6 2364.23  4866.1 2363.67  4907.1 2359.15
  4915.7 2357.83  4920.8 2357.86  4937.8 2356.46  4992.3 2355.12  4999.3 2354.38
  5019.6 2353.19  5060.4 2353.39  5099.1 2352.01  5099.3 2351.51  5102.8 2351.51
  5103.1 2352.01  5117.9 2352.41  5123.0 2352.03  5152.0 2353.62  5162.2 2354.50
  5169.8 2356.58  5174.9 2355.51  5182.6 2358.74  5192.7 2361.07  5213.1 2365.15
  5221.7 2367.41  5226.8 2367.52  5233.5 2369.02  5242.7 2371.75  5246.9 2371.75
#Mann=3,-1,0
  4806.9    0.07       0  5099.1    0.07       0  5103.1    0.07       0
Bank Sta=5099.1,5103.1
Exp/Cntr=0.3,0.1

Type RM Length L Ch R = 1,7388,212,212,212
BEGIN DESCRIPTION:
elmc750
END DESCRIPTION:
XS GIS Cut Line= 3
      1500659.72      6760279.22      1500830.31      6760057.84
      1500895.18      6759721.83
#Sta/Elev= 30
  4724.0 2366.49  4786.2 2361.80  4821.5 2358.37  4842.3 2357.08  4856.8 2355.25
  4906.6 2352.91  4950.1 2352.01  4956.5 2351.62  4976.0 2349.09  4976.3 2348.59
  4979.8 2348.59  4980.0 2349.09  5000.0 2349.86  5013.5 2349.58  5074.6 2350.46
  5115.4 2349.31  5135.7 2350.00  5145.9 2351.22  5155.6 2353.03  5160.6 2353.04
  5166.3 2354.77  5176.5 2356.73  5212.5 2362.15  5227.4 2362.80  5264.3 2366.17
  5269.4 2365.75  5316.2 2369.22  5321.3 2368.78  5329.2 2369.18  5345.7 2370.97
#Mann=3,-1,0
  4724.0    0.07       0  4976.0    0.07       0  4980.0    0.07       0
Bank Sta=4976,4980
Exp/Cntr=0.3,0.1

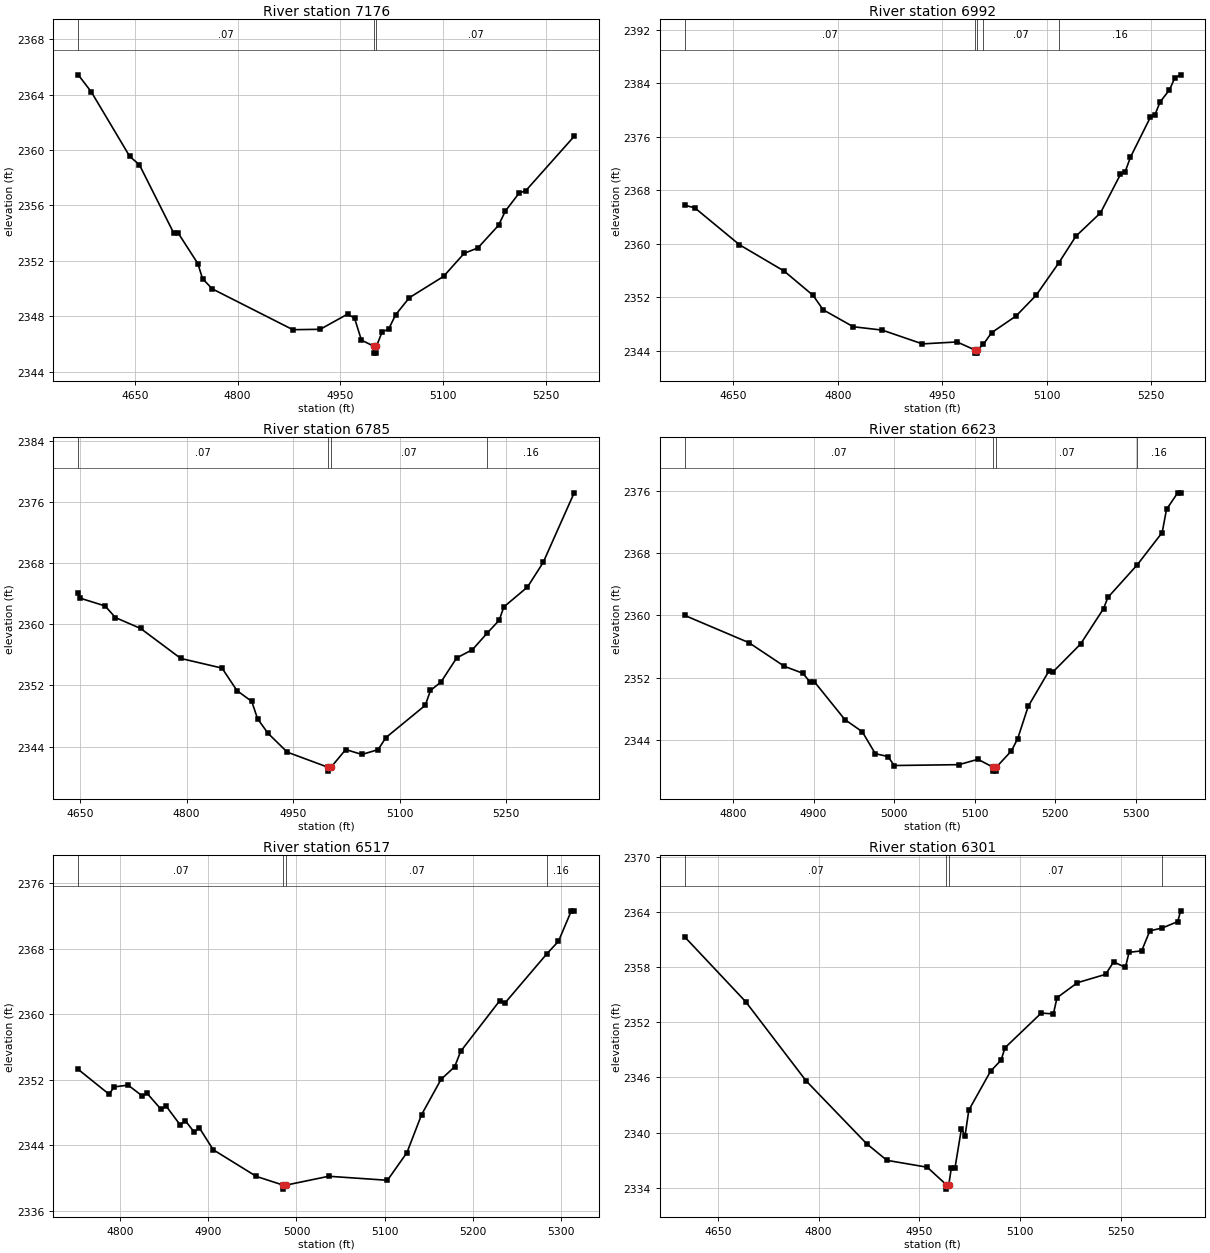
Type RM Length L Ch R = 1,7176,184,184,184
BEGIN DESCRIPTION:
elmc749
END DESCRIPTION:
XS GIS Cut Line= 3
      1500793.88      6760353.38      1500998.28      6760124.25
      1500990.47      6759707.57
#Sta/Elev= 30
  4567.3 2365.42  4586.4 2364.19  4642.4 2359.54  4656.6 2358.93  4706.8 2353.99
  4713.5 2353.98  4741.9 2351.80  4748.7 2350.72  4762.8 2349.98  4880.6 2347.03
  4920.6 2347.06  4960.6 2348.16  4970.6 2347.86  4980.6 2346.28  4998.6 2345.84
  4998.9 2345.34  5002.4 2345.34  5002.6 2345.84  5010.6 2346.84  5020.6 2347.10
  5030.6 2348.11  5050.6 2349.34  5100.6 2350.88  5130.6 2352.54  5150.6 2352.93
  5180.7 2354.56  5190.7 2355.59  5210.7 2356.88  5220.7 2357.07  5291.1 2360.98
#Mann=3,-1,0
  4567.3    0.07       0  4998.6    0.07       0  5002.6    0.07       0
Bank Sta=4998.6,5002.6
Exp/Cntr=0.3,0.1

Type RM Length L Ch R = 1,6992,207,207,207
BEGIN DESCRIPTION:
elmc748
END DESCRIPTION:
XS GIS Cut Line= 3
      1500802.96      6760375.55      1501131.09      6760115.13
      1501357.68      6759928.91
#Sta/Elev= 30
  4579.9 2365.75  4594.5 2365.35  4658.6 2359.84  4722.7 2355.91  4764.3 2352.28
  4778.7 2350.13  4822.0 2347.59  4863.6 2347.09  4921.3 2345.03  4971.0 2345.32
  4996.1 2344.15  4996.4 2343.65  4999.9 2343.65  5000.1 2344.15  5008.8 2344.96
  5020.6 2346.70  5055.8 2349.20  5084.5 2352.28  5116.8 2357.08  5141.8 2361.13
  5177.0 2364.60  5205.7 2370.35  5212.2 2370.68  5220.1 2372.93  5248.7 2378.90
  5255.2 2379.26  5262.7 2381.19  5276.0 2382.97  5283.9 2384.79  5292.1 2385.23
#Mann=5,-1,0
  4579.9    0.07       0  4996.1    0.07       0  5000.1    0.07       0
  5008.8    0.07       0  5116.8    0.16       0
Bank Sta=4996.1,5000.1
Exp/Cntr=0.3,0.1

Type RM Length L Ch R = 1,6785,162,162,162
BEGIN DESCRIPTION:
elmc747
END DESCRIPTION:
XS GIS Cut Line= 3
      1500869.39      6760495.33      1501148.02      6760287.01
      1501464.38      6760137.29
#Sta/Elev= 30
  4647.5 2364.13  4649.8 2363.42  4685.3 2362.39  4699.9 2360.87  4735.3 2359.45
  4791.9 2355.53  4849.9 2354.27  4870.8 2351.34  4891.7 2349.92  4899.9 2347.65
  4914.5 2345.76  4941.7 2343.29  4999.2 2341.31  4999.4 2340.81  5003.2 2341.31
  5023.9 2343.63  5046.7 2342.99  5069.4 2343.61  5080.6 2345.20  5135.9 2349.41
  5143.2 2351.35  5158.0 2352.45  5180.1 2355.60  5202.3 2356.68  5222.6 2358.80
  5239.8 2360.51  5246.5 2362.27  5279.7 2364.86  5301.8 2368.07  5345.4 2377.17
#Mann=4,-1,0
  4647.5    0.07       0  4999.2    0.07       0  5003.2    0.07       0
  5222.6    0.16       0
Bank Sta=4999.2,5003.2
Exp/Cntr=0.3,0.1

Type RM Length L Ch R = 1,6623,106,106,106
BEGIN DESCRIPTION:
elmc746
END DESCRIPTION:
XS GIS Cut Line= 3
      1500926.68      6760539.60      1501145.41      6760418.52
      1501496.99      6760318.25
#Sta/Elev= 30
  4740.0 2359.98  4819.7 2356.48  4863.8 2353.44  4886.7 2352.55  4895.3 2351.46
  4901.0 2351.46  4938.8 2346.61  4960.5 2345.04  4976.6 2342.23  4992.4 2341.86
  5000.0 2340.71  5080.5 2340.82  5104.0 2341.51  5122.8 2340.49  5123.0 2339.99
  5126.5 2339.99  5126.8 2340.49  5145.6 2342.59  5153.4 2344.17  5166.4 2348.30
  5192.4 2352.89  5197.6 2352.77  5231.4 2356.30  5259.9 2360.84  5265.3 2362.28
  5301.7 2366.46  5332.7 2370.61  5338.1 2373.59  5352.0 2375.71  5355.6 2375.71
#Mann=4,-1,0
  4740.0    0.07       0  5122.8    0.07       0  5126.8    0.07       0
  5301.7    0.16       0
Bank Sta=5122.8,5126.8
Exp/Cntr=0.3,0.1

Type RM Length L Ch R = 1,6517,216,216,216
BEGIN DESCRIPTION:
elmc745
END DESCRIPTION:
XS GIS Cut Line= 3
      1500999.60      6760620.33      1501198.80      6760507.06
      1501495.64      6760354.73
#Sta/Elev= 30
  4752.3 2353.29  4787.3 2350.26  4793.1 2351.15  4808.9 2351.37  4824.8 2350.06
  4830.6 2350.35  4846.4 2348.40  4852.2 2348.79  4868.0 2346.51  4873.8 2347.03
  4883.9 2345.63  4889.7 2346.16  4905.5 2343.48  4954.5 2340.22  4984.6 2339.17
  4984.8 2338.67  4988.6 2339.17  5036.6 2340.24  5103.2 2339.75  5125.3 2343.12
  5141.9 2347.75  5164.1 2352.08  5179.5 2353.61  5186.3 2355.49  5230.7 2361.68
  5236.3 2361.36  5284.1 2367.40  5297.3 2368.93  5311.9 2372.65  5315.1 2372.65
#Mann=4,-1,0
  4752.3    0.07       0  4984.6    0.07       0  4988.6    0.07       0
  5284.1    0.16       0
Bank Sta=4984.6,4988.6
Exp/Cntr=0.3,0.1

Type RM Length L Ch R = 1,6301,174,174,174
BEGIN DESCRIPTION:
elmc744
END DESCRIPTION:
XS GIS Cut Line= 3
      1500904.54      6760652.89      1501301.66      6760680.24
      1501617.58      6760552.83
#Sta/Elev= 30
  4600.5 2361.28  4691.2 2354.25  4781.4 2345.63  4871.6 2338.80  4901.7 2337.00
  4961.8 2336.25  4989.9 2334.37  4990.1 2333.87  4993.9 2334.37  4997.7 2336.17
  5003.1 2336.17  5012.7 2340.42  5018.1 2339.65  5023.7 2342.45  5056.1 2346.68
  5071.8 2347.89  5077.6 2349.23  5131.6 2353.00  5149.7 2352.91  5155.1 2354.67
  5185.5 2356.30  5227.5 2357.21  5239.4 2358.56  5257.0 2357.96  5262.4 2359.60
  5281.2 2359.76  5293.3 2361.93  5312.0 2362.25  5334.9 2362.94  5339.2 2364.11
#Mann=4,-1,0
  4600.5    0.07       0  4989.9    0.07       0  4993.9    0.07       0
  5312.0    0.16       0
Bank Sta=4989.9,4993.9
Exp/Cntr=0.3,0.1

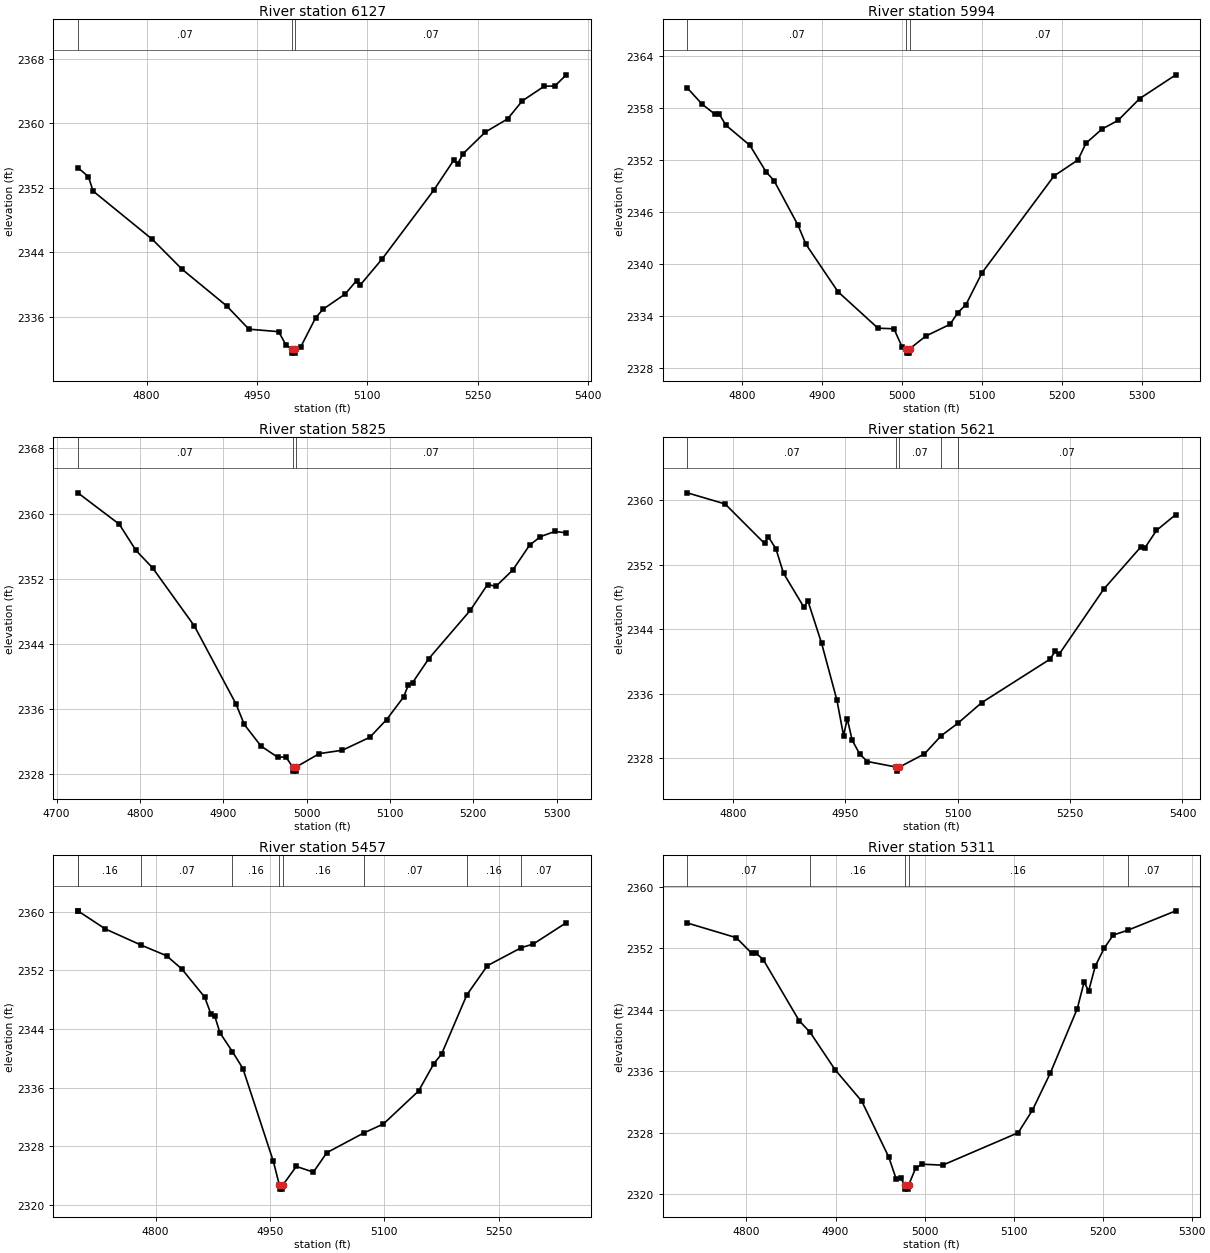
Type RM Length L Ch R = 1,6127,133,133,133
BEGIN DESCRIPTION:
elmc743
END DESCRIPTION:
XS GIS Cut Line= 3
      1500964.44      6760801.33      1501260.00      6760839.09
      1501624.61      6760811.74
#Sta/Elev= 30
  4706.6 2354.51  4721.0 2353.38  4727.3 2351.60  4808.0 2345.60  4848.3 2341.90
  4908.8 2337.36  4939.0 2334.48  4979.4 2334.17  4989.4 2332.51  4997.5 2332.01
  4997.8 2331.51  5001.3 2331.51  5001.5 2332.01  5009.6 2332.31  5029.6 2335.88
  5039.7 2336.95  5069.7 2338.83  5085.4 2340.51  5090.4 2339.97  5119.9 2343.17
  5190.1 2351.70  5217.4 2355.44  5222.4 2354.96  5230.2 2356.25  5260.3 2358.92
  5290.4 2360.54  5310.4 2362.78  5340.5 2364.61  5354.5 2364.61  5370.2 2366.01
#Mann=3,-1,0
  4706.6    0.07       0  4997.5    0.07       0  5001.5    0.07       0
Bank Sta=4997.5,5001.5
Exp/Cntr=0.3,0.1

Type RM Length L Ch R = 1,5994,169,169,169
BEGIN DESCRIPTION:
elmc742
END DESCRIPTION:
XS GIS Cut Line= 3
      1500926.70      6760953.67      1501205.31      6760948.47
      1501537.31      6760953.67
#Sta/Elev= 30
  4731.8 2360.26  4750.1 2358.42  4766.5 2357.23  4771.5 2357.28  4780.1 2355.98
  4810.1 2353.66  4830.1 2350.63  4840.1 2349.62  4870.1 2344.49  4880.1 2342.28
  4920.1 2336.83  4970.1 2332.63  4990.1 2332.56  5000.1 2330.51  5005.8 2330.26
  5006.0 2329.76  5009.5 2329.76  5009.8 2330.26  5030.1 2331.73  5060.2 2333.07
  5070.2 2334.43  5080.2 2335.35  5100.2 2339.00  5190.2 2350.14  5220.2 2351.99
  5230.2 2353.91  5250.2 2355.54  5270.2 2356.53  5297.4 2359.05  5342.5 2361.78
#Mann=3,-1,0
  4731.8    0.07       0  5005.8    0.07       0  5009.8    0.07       0
Bank Sta=5005.8,5009.8
Exp/Cntr=0.3,0.1

Type RM Length L Ch R = 1,5825,204,204,204
BEGIN DESCRIPTION:
elmc741
END DESCRIPTION:
XS GIS Cut Line= 3
      1500925.31      6761089.09      1501197.50      6761089.09
      1501508.71      6761048.72
#Sta/Elev= 30
  4725.6 2362.55  4775.3 2358.70  4795.3 2355.49  4815.3 2353.34  4865.3 2346.23
  4915.3 2336.66  4925.3 2334.13  4945.3 2331.49  4965.3 2330.12  4975.3 2330.14
  4983.3 2328.91  4983.5 2328.41  4987.0 2328.41  4987.3 2328.91  5015.4 2330.56
  5042.9 2330.97  5075.9 2332.56  5096.1 2334.74  5116.3 2337.49  5122.1 2338.97
  5127.1 2339.25  5146.5 2342.19  5196.3 2348.12  5217.1 2351.30  5227.2 2351.08
  5247.4 2353.08  5267.5 2356.12  5280.5 2357.17  5297.8 2357.81  5311.6 2357.64
#Mann=3,-1,0
  4725.6    0.07       0  4983.3    0.07       0  4987.3    0.07       0
Bank Sta=4983.3,4987.3
Exp/Cntr=0.3,0.1

Type RM Length L Ch R = 1,5621,164,164,164
BEGIN DESCRIPTION:
elmc740
END DESCRIPTION:
XS GIS Cut Line= 3
      1500948.84      6761244.05      1501206.61      6761292.22
      1501590.38      6761225.87
#Sta/Elev= 30
  4739.4 2360.91  4789.8 2359.53  4842.4 2354.64  4847.5 2355.46  4857.6 2353.97
  4867.7 2350.95  4895.1 2346.71  4900.2 2347.54  4918.6 2342.25  4939.0 2335.21
  4947.8 2330.84  4952.8 2332.92  4959.3 2330.26  4969.5 2328.53  4979.7 2327.62
  5018.3 2326.93  5018.5 2326.43  5022.3 2326.93  5055.8 2328.57  5077.9 2330.80
  5100.6 2332.38  5131.9 2334.90  5223.3 2340.30  5230.1 2341.27  5235.2 2340.88
  5295.0 2348.98  5344.6 2354.22  5349.7 2354.06  5365.3 2356.25  5391.1 2358.22
#Mann=5,-1,0
  4739.4    0.07       0  5018.3    0.07       0  5022.3    0.07       0
  5077.9    0.16       0  5100.6    0.07       0
Bank Sta=5018.3,5022.3
Exp/Cntr=0.3,0.1

Type RM Length L Ch R = 1,5457,146,146,146
BEGIN DESCRIPTION:
elmc739
END DESCRIPTION:
XS GIS Cut Line= 3
      1500948.82      6761422.43      1501254.79      6761440.65
      1501588.16      6761413.31
#Sta/Elev= 30
  4697.9 2360.12  4698.0 2360.11  4734.1 2357.64  4780.8 2355.45  4814.3 2353.99
  4834.3 2352.19  4864.4 2348.34  4872.5 2346.05  4877.6 2345.75  4884.4 2343.47
  4900.8 2340.90  4914.5 2338.60  4954.5 2325.92  4962.5 2322.64  4962.8 2322.14
  4966.3 2322.14  4966.5 2322.64  4984.6 2325.24  5007.0 2324.46  5024.7 2327.12
  5072.9 2329.79  5099.0 2331.04  5145.1 2335.54  5165.2 2339.28  5175.2 2340.57
  5208.4 2348.65  5235.4 2352.64  5280.0 2355.10  5295.6 2355.59  5338.9 2358.50
#Mann=9,-1,0
  4697.9    0.07       0  4698.0    0.16       0  4780.8    0.07       0
  4900.8    0.16       0  4962.5    0.07       0  4966.5    0.16       0
  5072.9    0.07       0  5208.4    0.16       0  5280.0    0.07       0
Bank Sta=4962.5,4966.5
Exp/Cntr=0.3,0.1

Type RM Length L Ch R = 1,5311,203,203,203
BEGIN DESCRIPTION:
elmc738
END DESCRIPTION:
XS GIS Cut Line= 3
      1500990.45      6761553.93      1501254.79      6761586.49
      1501534.69      6761550.03
#Sta/Elev= 30
  4733.6 2355.30  4788.6 2353.39  4805.7 2351.38  4810.8 2351.37  4818.8 2350.54
  4859.1 2342.59  4871.6 2341.04  4899.4 2336.21  4929.6 2332.07  4959.8 2324.81
  4968.1 2321.97  4973.2 2322.08  4978.0 2321.13  4978.2 2320.63  4981.7 2320.63
  4982.0 2321.13  4990.1 2323.38  4997.5 2323.88  5020.3 2323.75  5105.2 2327.98
  5121.2 2330.92  5141.3 2335.76  5171.6 2344.16  5179.2 2347.61  5184.3 2346.45
  5191.8 2349.69  5201.8 2352.03  5211.9 2353.73  5228.5 2354.37  5282.2 2356.89
#Mann=5,-1,0
  4733.6    0.07       0  4871.6    0.16       0  4978.0    0.07       0
  4982.0    0.16       0  5228.5    0.07       0
Bank Sta=4978,4982
Exp/Cntr=0.3,0.1

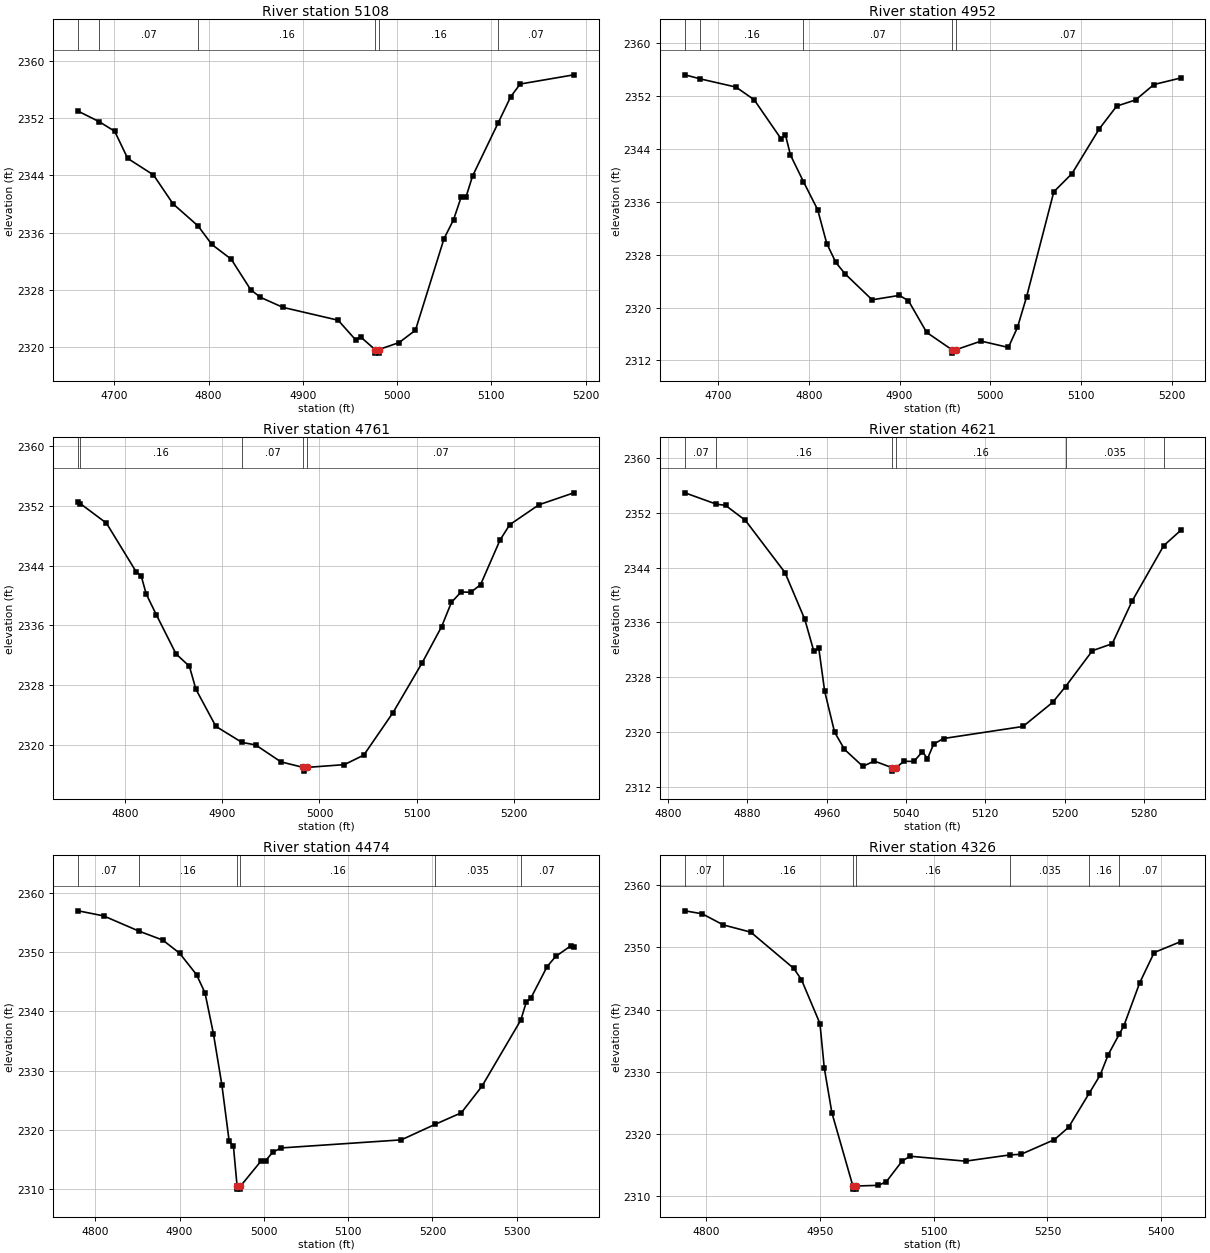
Type RM Length L Ch R = 1,5108,156,156,156
BEGIN DESCRIPTION:
elmc370
END DESCRIPTION:
XS GIS Cut Line= 3
      1500977.46      6761690.66      1501305.71      6761772.94
      1501491.49      6761746.87
#Sta/Elev= 30
  4661.6 2353.00  4683.7 2351.54  4700.3 2350.19  4714.1 2346.39  4741.5 2344.07
  4762.2 2340.03  4788.8 2336.93  4803.4 2334.34  4824.0 2332.27  4844.6 2328.01
  4854.9 2326.94  4878.8 2325.53  4937.4 2323.73  4956.0 2320.98  4961.2 2321.40
  4976.6 2319.62  4976.9 2319.12  4980.4 2319.12  4980.6 2319.62  5002.2 2320.60
  5019.5 2322.33  5049.8 2335.14  5059.9 2337.79  5068.2 2341.04  5073.3 2341.05
  5080.1 2343.92  5107.2 2351.34  5120.5 2355.00  5130.6 2356.80  5187.6 2358.09
#Mann=6,-1,0
  4661.6    0.16       0  4683.7    0.07       0  4788.8    0.16       0
  4976.6    0.07       0  4980.6    0.16       0  5107.2    0.07       0
Bank Sta=4976.6,4980.6
Exp/Cntr=0.3,0.1

Type RM Length L Ch R = 1,4952,191,191,191
BEGIN DESCRIPTION:
elmc737
END DESCRIPTION:
XS GIS Cut Line= 3
      1500918.85      6761927.63      1501260.00      6761913.31
      1501464.45      6761927.63
#Sta/Elev= 30
  4663.5 2355.18  4680.2 2354.57  4719.7 2353.33  4739.7 2351.42  4769.3 2345.53
  4774.3 2346.08  4779.8 2343.05  4794.1 2339.03  4809.8 2334.78  4819.8 2329.68
  4829.8 2326.82  4839.8 2325.12  4869.8 2321.17  4899.9 2321.84  4909.9 2321.02
  4929.9 2316.25  4957.9 2313.61  4958.2 2313.11  4961.9 2313.61  4989.9 2314.93
  5020.0 2313.97  5030.0 2316.99  5040.0 2321.58  5070.1 2337.50  5090.2 2340.26
  5120.2 2347.01  5139.4 2350.45  5160.3 2351.39  5180.4 2353.71  5209.9 2354.70
#Mann=5,-1,0
  4663.5    0.07       0  4680.2    0.16       0  4794.1    0.07       0
  4957.9    0.07       0  4961.9    0.07       0
Bank Sta=4957.9,4961.9
Exp/Cntr=0.3,0.1

Type RM Length L Ch R = 1,4761,140,140,140
BEGIN DESCRIPTION:
elmc736
END DESCRIPTION:
XS GIS Cut Line= 3
      1500956.59      6762039.61      1501189.68      6762089.09
      1501460.89      6762091.69
#Sta/Elev= 30
  4752.0 2352.50  4754.1 2352.30  4781.0 2349.68  4811.5 2343.18  4816.7 2342.63
  4821.9 2340.19  4832.2 2337.43  4852.6 2332.15  4866.3 2330.50  4873.0 2327.42
  4893.5 2322.45  4920.3 2320.30  4934.4 2319.96  4960.4 2317.69  4983.3 2316.95
  4983.6 2316.45  4987.3 2316.95  5025.6 2317.32  5045.6 2318.60  5075.6 2324.29
  5105.6 2330.97  5125.6 2335.82  5135.6 2339.05  5145.6 2340.46  5155.6 2340.41
  5165.6 2341.43  5185.6 2347.41  5195.6 2349.47  5225.6 2352.14  5261.5 2353.74
#Mann=5,-1,0
  4752.0    0.07       0  4754.1    0.16       0  4920.3    0.07       0
  4983.3    0.07       0  4987.3    0.07       0
Bank Sta=4983.3,4987.3
Exp/Cntr=0.3,0.1

Type RM Length L Ch R = 1,4621,147,147,147
BEGIN DESCRIPTION:
elmc369
END DESCRIPTION:
XS GIS Cut Line= 3
      1500924.09      6762190.65      1501107.06      6762193.86
      1501424.03      6762189.35
#Sta/Elev= 30
  4817.0 2354.94  4848.7 2353.28  4857.9 2353.11  4877.9 2350.92  4917.9 2343.28
  4937.9 2336.43  4947.0 2331.77  4952.0 2332.20  4957.9 2325.94  4967.9 2319.96
  4977.9 2317.43  4996.5 2314.94  5007.9 2315.73  5025.9 2314.75  5026.2 2314.25
  5029.9 2314.75  5037.9 2315.70  5047.9 2315.66  5056.6 2317.10  5061.6 2316.06
  5067.9 2318.21  5077.9 2319.02  5158.0 2320.78  5188.0 2324.32  5200.9 2326.61
  5228.0 2331.86  5248.0 2332.88  5268.0 2339.10  5299.9 2347.21  5317.0 2349.44
#Mann=6,-1,0
  4817.0    0.07       0  4848.7    0.16       0  5025.9    0.07       0
  5029.9    0.16       0  5200.9   0.035       0  5299.9    0.07       0
Bank Sta=5025.9,5029.9
Exp/Cntr=0.3,0.1

Type RM Length L Ch R = 1,4474,148,148,148
BEGIN DESCRIPTION:
elmc735
END DESCRIPTION:
XS GIS Cut Line= 3
      1500885.00      6762356.02      1501103.75      6762340.39
      1501466.20      6762272.84
#Sta/Elev= 30
  4779.7 2356.92  4809.8 2356.07  4851.6 2353.51  4880.0 2351.99  4900.0 2349.78
  4920.1 2346.16  4930.1 2343.11  4940.1 2336.23  4950.1 2327.63  4958.8 2318.10
  4963.8 2317.33  4968.2 2310.53  4968.4 2310.03  4971.9 2310.03  4972.2 2310.53
  4997.1 2314.85  5002.2 2314.85  5010.5 2316.26  5020.6 2316.97  5163.0 2318.33
  5203.5 2320.97  5234.2 2322.89  5258.7 2327.37  5304.7 2338.49  5311.4 2341.60
  5316.5 2342.16  5336.0 2347.53  5346.1 2349.23  5364.1 2351.02  5367.7 2350.80
#Mann=6,-1,0
  4779.7    0.07       0  4851.6    0.16       0  4968.2    0.07       0
  4972.2    0.16       0  5203.5   0.035       0  5304.7    0.07       0
Bank Sta=4968.2,4972.2
Exp/Cntr=0.3,0.1

Type RM Length L Ch R = 1,4326,101,101,101
BEGIN DESCRIPTION:
elmc734
END DESCRIPTION:
XS GIS Cut Line= 3
      1500882.35      6762512.27      1501108.96      6762487.53
      1501516.54      6762363.82
#Sta/Elev= 30
  4771.8 2355.89  4794.6 2355.41  4822.2 2353.63  4858.6 2352.46  4915.3 2346.63
  4925.4 2344.83  4949.9 2337.75  4955.5 2330.67  4965.6 2323.41  4993.3 2311.62
  4993.5 2311.12  4997.0 2311.12  4997.3 2311.62  5027.0 2311.73  5037.4 2312.31
  5058.3 2315.64  5068.8 2316.41  5141.9 2315.62  5200.7 2316.63  5215.1 2316.72
  5259.2 2319.08  5277.8 2321.06  5305.0 2326.53  5319.6 2329.48  5330.2 2332.76
  5345.0 2336.10  5350.9 2337.43  5371.8 2344.34  5390.8 2349.18  5425.7 2350.93
#Mann=7,-1,0
  4771.8    0.07       0  4822.2    0.16       0  4993.3    0.07       0
  4997.3    0.16       0  5200.7   0.035       0  5305.0    0.16       0
  5345.0    0.07       0
Bank Sta=4993.3,4997.3
Exp/Cntr=0.3,0.1