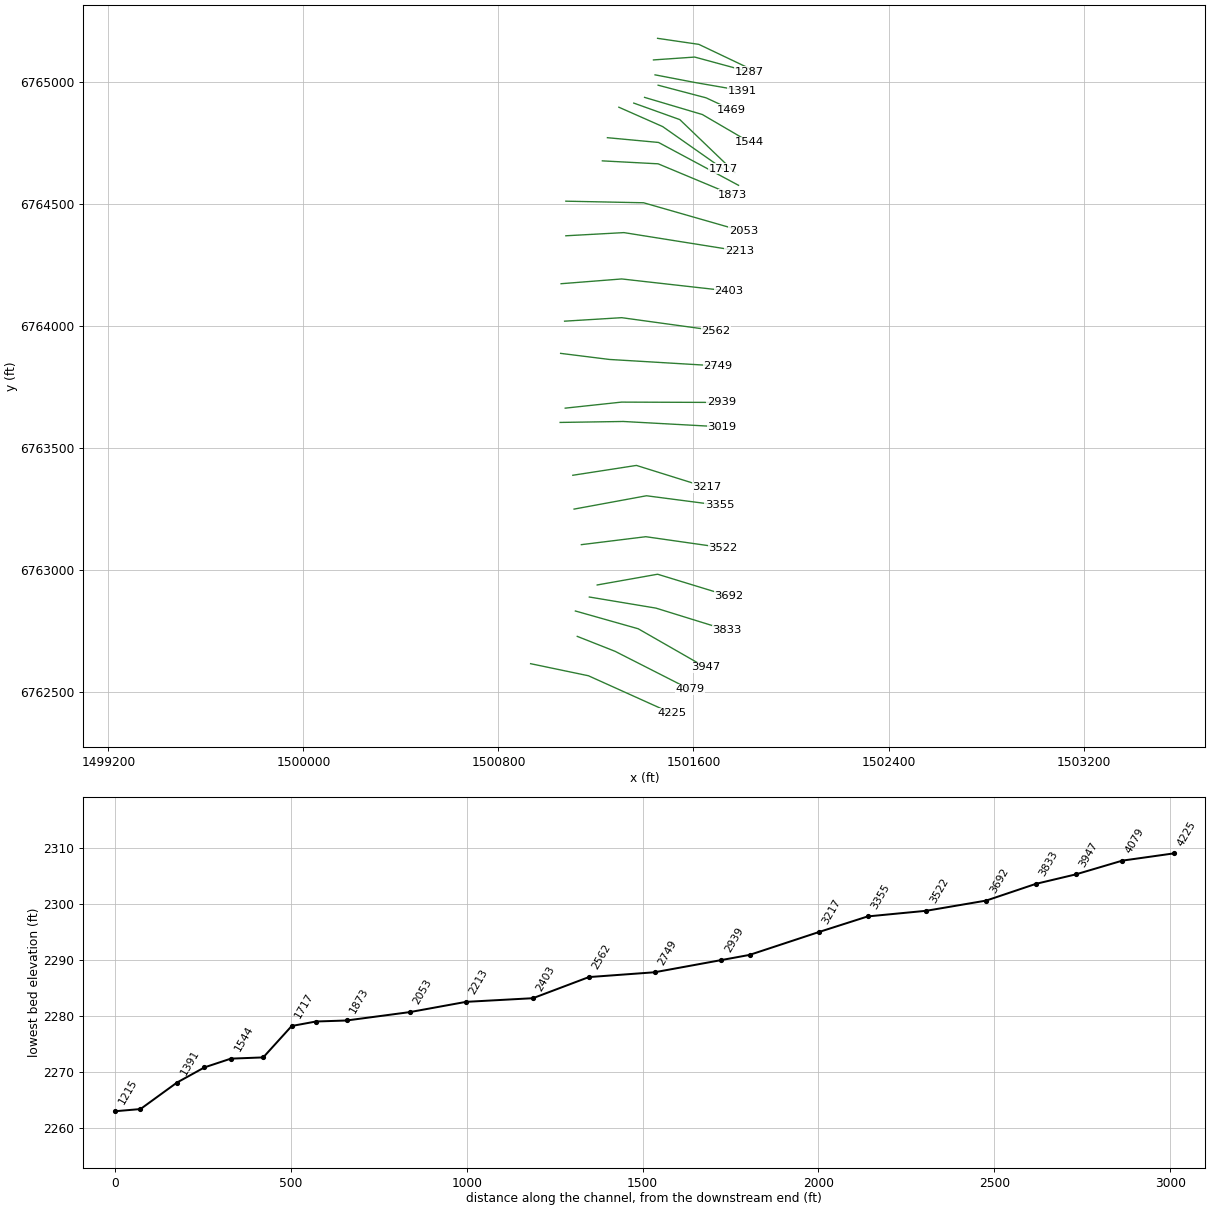
HEC-RAS study Elm 35.prj: Elm 35 Base Level Engineering

--- Elm 35.g01 (geometry) --- (continued)

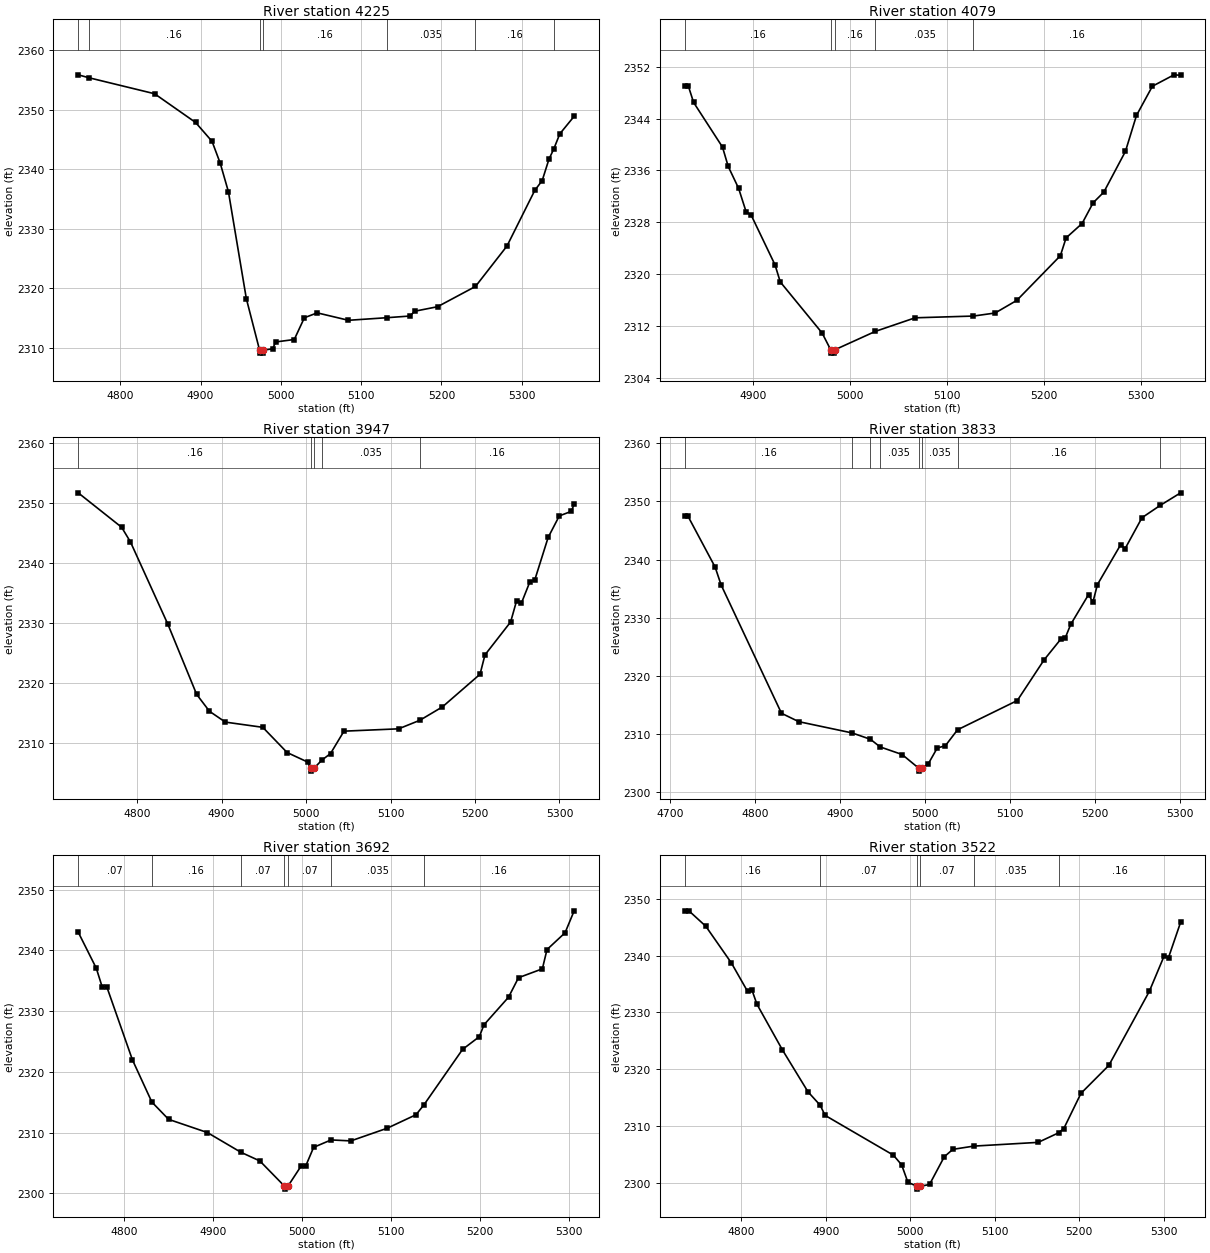
Type RM Length L Ch R = 1,4225,146,146,146
BEGIN DESCRIPTION:
elmc733
END DESCRIPTION:
XS GIS Cut Line= 3
      1500931.87      6762615.13      1501168.85      6762565.65
      1501511.28      6762411.30
#Sta/Elev= 30
  4747.6 2355.90  4761.2 2355.40  4842.7 2352.72  4893.8 2347.89  4914.3 2344.71
  4924.5 2341.03  4934.7 2336.24  4957.0 2318.27  4973.5 2309.61  4973.8 2309.11
  4977.3 2309.11  4977.5 2309.61  4989.7 2309.83  4993.6 2310.99  5016.7 2311.40
  5029.3 2315.06  5045.3 2315.88  5084.2 2314.63  5132.5 2315.07  5161.0 2315.35
  5166.5 2316.15  5195.1 2316.91  5242.4 2320.32  5281.6 2327.11  5316.3 2336.48
  5325.5 2338.12  5333.9 2341.71  5340.0 2343.46  5347.4 2345.97  5365.3 2348.93
#Mann=7,-1,0
  4747.6    0.07       0  4761.2    0.16       0  4973.5    0.07       0
  4977.5    0.16       0  5132.5   0.035       0  5242.4    0.16       0
  5340.0    0.07       0
Bank Sta=4973.5,4977.5
Exp/Cntr=0.3,0.1

Type RM Length L Ch R = 1,4079,132,132,132
BEGIN DESCRIPTION:
elmc732
END DESCRIPTION:
XS GIS Cut Line= 3
      1501123.25      6762727.12      1501278.23      6762665.91
      1501585.55      6762509.65
#Sta/Elev= 30
  4829.8 2349.11  4833.4 2349.11  4839.0 2346.50  4868.8 2339.61  4874.7 2336.62
  4885.4 2333.25  4893.1 2329.65  4898.5 2329.07  4922.9 2321.46  4928.4 2318.80
  4971.5 2310.93  4980.4 2308.32  4980.6 2307.82  4984.1 2307.82  4984.4 2308.32
  5026.5 2311.18  5067.4 2313.27  5127.6 2313.54  5149.9 2314.01  5172.3 2315.96
  5217.2 2322.85  5223.1 2325.60  5239.6 2327.82  5251.0 2331.02  5262.0 2332.66
  5284.3 2338.95  5295.7 2344.50  5312.1 2349.00  5334.4 2350.76  5341.2 2350.69
#Mann=5,-1,0
  4829.8    0.16       0  4980.4    0.07       0  4984.4    0.16       0
  5026.5   0.035       0  5127.6    0.16       0
Bank Sta=4980.4,4984.4
Exp/Cntr=0.3,0.1

Type RM Length L Ch R = 1,3947,114,114,114
BEGIN DESCRIPTION:
elmc731
END DESCRIPTION:
XS GIS Cut Line= 3
      1501115.50      6762831.27      1501373.28      6762758.36
      1501650.27      6762599.71
#Sta/Elev= 30
  4730.3 2351.75  4781.7 2346.01  4792.1 2343.58  4836.5 2329.83  4870.5 2318.16
  4885.7 2315.34  4904.5 2313.54  4948.8 2312.67  4977.6 2308.47  5002.1 2306.87
  5005.5 2305.87  5005.7 2305.37  5009.5 2305.87  5018.8 2307.21  5029.0 2308.30
  5044.9 2312.03  5109.6 2312.42  5134.7 2313.84  5161.5 2316.08  5206.0 2321.52
  5211.8 2324.74  5242.2 2330.23  5249.2 2333.73  5254.9 2333.35  5265.0 2336.92
  5270.8 2337.24  5286.6 2344.31  5299.8 2347.90  5313.9 2348.66  5317.4 2349.83
#Mann=5,-1,0
  4730.3    0.16       0  5005.5    0.07       0  5009.5    0.16       0
  5018.8   0.035       0  5134.7    0.16       0
Bank Sta=5005.5,5009.5
Exp/Cntr=0.3,0.1

Type RM Length L Ch R = 1,3833,141,141,141
BEGIN DESCRIPTION:
elmc730
END DESCRIPTION:
XS GIS Cut Line= 3
      1501172.75      6762888.57      1501446.20      6762843.00
      1501738.39      6762752.50
#Sta/Elev= 30
  4717.5 2347.51  4721.2 2347.51  4753.3 2338.72  4760.3 2335.67  4831.3 2313.61
  4851.6 2312.17  4914.4 2310.23  4935.9 2309.14  4947.3 2307.83  4973.2 2306.52
  4992.7 2304.17  4993.0 2303.67  4996.7 2304.17  5003.9 2304.92  5014.4 2307.63
  5024.1 2308.05  5038.3 2310.77  5108.6 2315.80  5140.0 2322.77  5159.7 2326.34
  5164.9 2326.54  5171.4 2328.88  5192.3 2333.98  5197.5 2332.72  5202.8 2335.72
  5230.2 2342.59  5235.4 2341.91  5255.2 2347.21  5276.6 2349.32  5300.6 2351.48
#Mann=8,-1,0
  4717.5    0.16       0  4914.4    0.07       0  4935.9    0.16       0
  4947.3   0.035       0  4992.7   0.035       0  4996.7   0.035       0
  5038.3    0.16       0  5276.6    0.07       0
Bank Sta=4992.7,4996.7
Exp/Cntr=0.3,0.1

Type RM Length L Ch R = 1,3692,170,170,170
BEGIN DESCRIPTION:
elmc368
END DESCRIPTION:
XS GIS Cut Line= 3
      1501205.04      6762938.01      1501452.75      6762982.06
      1501744.80      6762892.74
#Sta/Elev= 30
  4748.4 2343.00  4768.7 2337.06  4775.3 2333.99  4780.4 2334.04  4809.3 2321.97
  4831.1 2315.03  4849.9 2312.18  4893.4 2310.01  4931.1 2306.76  4952.4 2305.33
  4980.0 2301.19  4980.2 2300.69  4984.0 2301.19  4998.6 2304.46  5003.8 2304.46
  5012.8 2307.57  5032.4 2308.79  5054.6 2308.63  5095.3 2310.71  5127.8 2312.94
  5136.8 2314.59  5180.1 2323.70  5198.9 2325.79  5204.1 2327.74  5231.7 2332.29
  5242.9 2335.50  5269.7 2336.96  5274.9 2340.13  5295.2 2342.90  5305.4 2346.51
#Mann=7,-1,0
  4748.4    0.07       0  4831.1    0.16       0  4931.1    0.07       0
  4980.0    0.07       0  4984.0    0.07       0  5032.4   0.035       0
  5136.8    0.16       0
Bank Sta=4980,4984
Exp/Cntr=0.3,0.1

Type RM Length L Ch R = 1,3522,167,167,167
BEGIN DESCRIPTION:
elmc729
END DESCRIPTION:
XS GIS Cut Line= 3
      1501140.18      6763103.41      1501404.53      6763135.97
      1501721.76      6763090.65
#Sta/Elev= 30
  4733.1 2347.91  4738.1 2347.91  4758.1 2345.19  4788.3 2338.74  4807.5 2333.72
  4812.5 2334.03  4818.6 2331.45  4848.8 2323.39  4879.0 2316.02  4893.5 2313.64
  4899.2 2311.87  4980.0 2304.86  4989.8 2303.15  4997.2 2300.08  5008.0 2299.37
  5008.3 2298.87  5012.0 2299.37  5022.8 2299.69  5040.3 2304.58  5050.4 2305.88
  5075.1 2306.45  5151.4 2307.11  5175.5 2308.79  5181.7 2309.55  5202.0 2315.75
  5234.9 2320.66  5282.8 2333.70  5300.6 2340.02  5305.6 2339.68  5319.9 2345.90
#Mann=6,-1,0
  4733.1    0.16       0  4893.5    0.07       0  5008.0    0.07       0
  5012.0    0.07       0  5075.1   0.035       0  5175.5    0.16       0
Bank Sta=5008,5012
Exp/Cntr=0.3,0.1

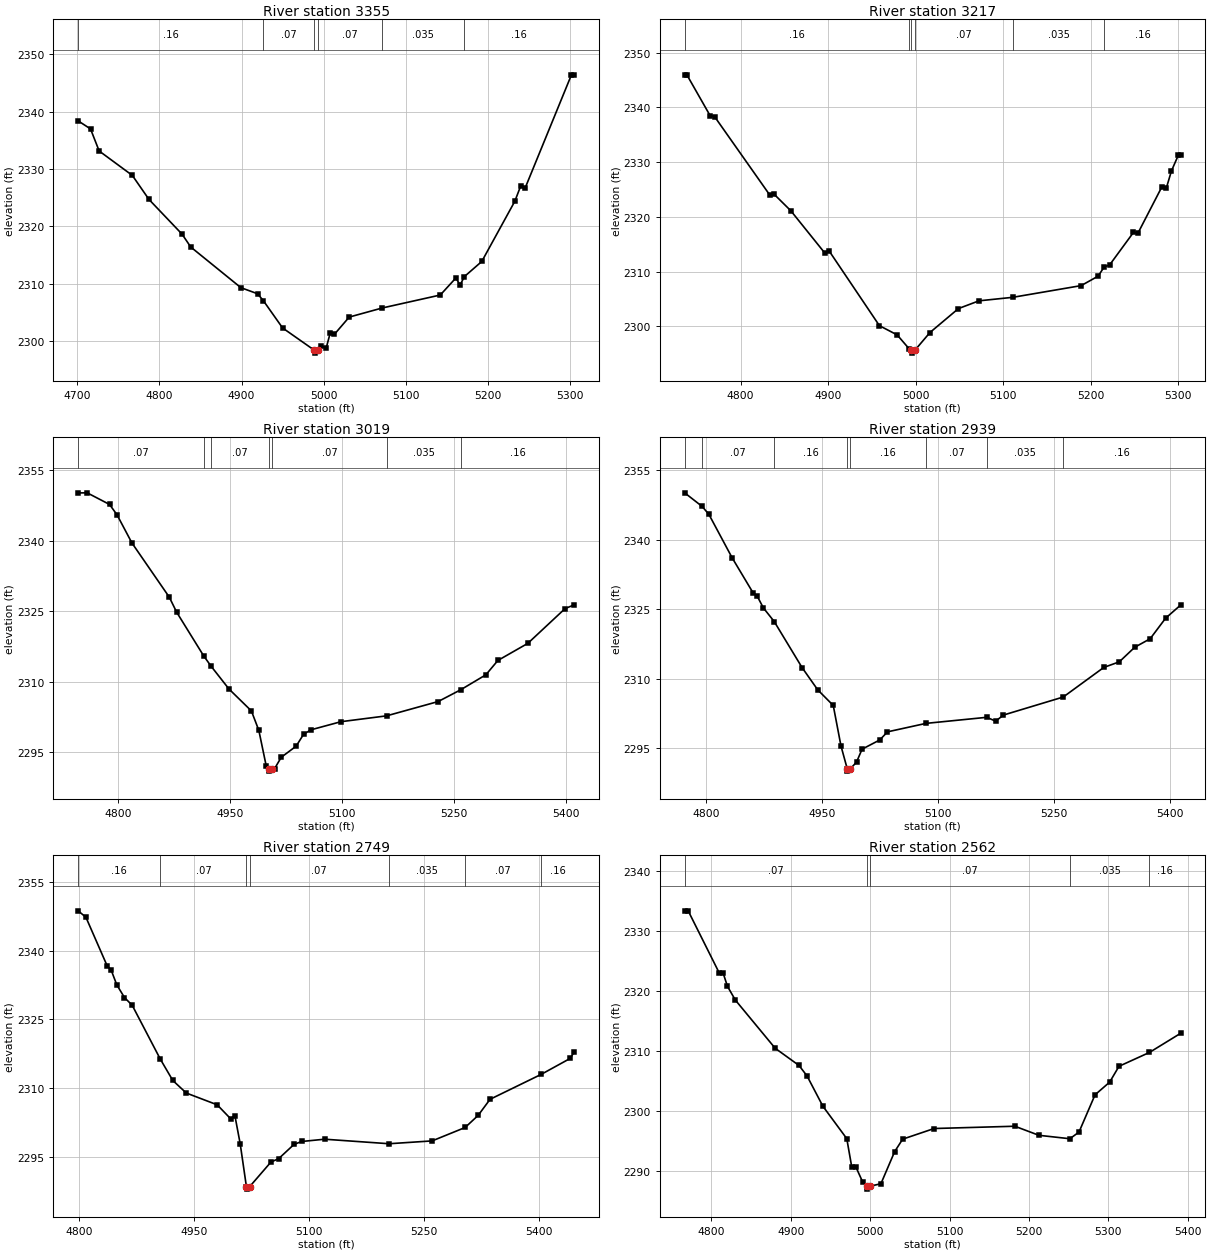
Type RM Length L Ch R = 1,3355,138,138,138
BEGIN DESCRIPTION:
elmc728
END DESCRIPTION:
XS GIS Cut Line= 3
      1501110.23      6763249.24      1501407.13      6763303.93
      1501706.59      6763264.87
#Sta/Elev= 30
  4701.1 2338.38  4716.1 2336.98  4726.6 2333.13  4767.0 2328.87  4787.3 2324.67
  4827.6 2318.61  4838.1 2316.38  4899.2 2309.28  4919.5 2308.22  4926.6 2307.00
  4950.0 2302.25  4988.7 2298.36  4988.9 2297.86  4992.7 2298.36  4996.8 2299.13
  5003.0 2298.73  5008.1 2301.43  5013.1 2301.15  5031.1 2304.15  5071.1 2305.73
  5142.0 2308.00  5161.0 2310.98  5166.1 2309.73  5171.3 2311.21  5192.5 2313.85
  5232.8 2324.37  5240.0 2327.06  5245.1 2326.59  5301.7 2346.42  5305.0 2346.42
#Mann=6,-1,0
  4701.1    0.16       0  4926.6    0.07       0  4988.7    0.07       0
  4992.7    0.07       0  5071.1   0.035       0  5171.3    0.16       0
Bank Sta=4988.7,4992.7
Exp/Cntr=0.3,0.1

Type RM Length L Ch R = 1,3217,198,198,198
BEGIN DESCRIPTION:
elmc367
END DESCRIPTION:
XS GIS Cut Line= 3
      1501105.00      6763388.00      1501365.89      6763428.37
      1501655.00      6763338.00
#Sta/Elev= 30
  4736.0 2345.96  4738.5 2345.96  4765.0 2338.52  4770.1 2338.34  4833.1 2324.03
  4838.2 2324.14  4857.4 2321.10  4896.2 2313.38  4901.2 2313.75  4958.6 2300.11
  4978.9 2298.42  4992.9 2295.82  4995.0 2295.59  4995.3 2295.09  4999.0 2295.59
  5016.4 2298.86  5048.9 2303.23  5072.4 2304.65  5111.0 2305.29  5189.2 2307.43
  5208.6 2309.16  5215.6 2310.86  5221.7 2311.20  5249.0 2317.16  5254.2 2317.04
  5281.4 2325.46  5286.7 2325.33  5292.4 2328.39  5300.3 2331.28  5302.9 2331.28
#Mann=6,-1,0
  4736.0    0.16       0  4992.9    0.07       0  4995.0    0.07       0
  4999.0    0.07       0  5111.0   0.035       0  5215.6    0.16       0
Bank Sta=4995,4999
Exp/Cntr=0.3,0.1

Type RM Length L Ch R = 1,3019,80,80,80
BEGIN DESCRIPTION:
elmc727
END DESCRIPTION:
XS GIS Cut Line= 3
      1501052.97      6763604.72      1501312.08      6763608.62
      1501717.04      6763586.49
#Sta/Elev= 30
  4746.1 2350.13  4758.1 2350.15  4788.1 2347.68  4798.1 2345.48  4818.1 2339.49
  4868.1 2327.99  4878.1 2324.76  4914.1 2315.53  4924.0 2313.33  4948.2 2308.44
  4978.2 2303.79  4988.2 2299.64  4998.2 2292.00  5002.2 2291.49  5002.4 2290.99
  5006.2 2291.49  5009.2 2291.49  5018.2 2293.93  5038.2 2296.30  5048.2 2298.83
  5058.2 2299.78  5098.3 2301.50  5159.4 2302.74  5228.5 2305.78  5258.7 2308.28
  5292.5 2311.47  5308.6 2314.52  5348.7 2318.15  5398.7 2325.55  5410.8 2326.33
#Mann=7,-1,0
  4746.1    0.07       0  4914.1    0.16       0  4924.0    0.07       0
  5002.2    0.07       0  5006.2    0.07       0  5159.4   0.035       0
  5258.7    0.16       0
Bank Sta=5002.2,5006.2
Exp/Cntr=0.3,0.1

Type RM Length L Ch R = 1,2939,190,190,190
BEGIN DESCRIPTION:
elmc726
END DESCRIPTION:
XS GIS Cut Line= 3
      1501073.83      6763663.31      1501304.27      6763688.05
      1501714.41      6763686.75
#Sta/Elev= 30
  4772.4 2350.15  4795.0 2347.21  4803.7 2345.51  4833.9 2336.10  4861.1 2328.51
  4866.1 2327.90  4874.2 2325.32  4888.3 2322.36  4924.4 2312.41  4944.6 2307.62
  4964.7 2304.25  4974.7 2295.51  4982.8 2290.57  4983.0 2290.07  4986.8 2290.57
  4994.8 2292.01  5002.0 2294.81  5024.9 2296.80  5034.9 2298.55  5084.8 2300.38
  5163.5 2301.69  5174.9 2300.85  5184.9 2302.17  5262.4 2306.07  5314.9 2312.46
  5334.9 2313.66  5354.9 2316.81  5374.9 2318.65  5394.9 2323.09  5414.3 2325.92
#Mann=8,-1,0
  4772.4    0.16       0  4795.0    0.07       0  4888.3    0.16       0
  4982.8    0.07       0  4986.8    0.16       0  5084.8    0.07       0
  5163.5   0.035       0  5262.4    0.16       0
Bank Sta=4982.8,4986.8
Exp/Cntr=0.3,0.1

Type RM Length L Ch R = 1,2749,187,187,187
BEGIN DESCRIPTION:
elmc366
END DESCRIPTION:
XS GIS Cut Line= 3
      1501055.02      6763888.00      1501254.77      6763863.07
      1501700.08      6763836.49
#Sta/Elev= 30
  4798.7 2348.71  4808.8 2347.29  4836.5 2336.68  4841.5 2335.85  4849.1 2332.52
  4859.1 2329.76  4869.2 2328.06  4905.9 2316.29  4922.2 2311.63  4939.8 2308.89
  4980.1 2306.32  4997.6 2303.28  5003.2 2303.98  5010.2 2297.76  5018.3 2288.39
  5018.5 2287.89  5022.3 2288.39  5050.3 2293.81  5060.3 2294.54  5080.4 2297.66
  5090.4 2298.30  5120.4 2298.80  5204.5 2297.81  5260.7 2298.43  5303.8 2301.36
  5320.8 2304.01  5336.3 2307.52  5403.2 2312.98  5441.0 2316.46  5446.1 2317.87
#Mann=7,-1,0
  4798.7    0.16       0  4905.9    0.07       0  5018.3    0.07       0
  5022.3    0.07       0  5204.5   0.035       0  5303.8    0.07       0
  5403.2    0.16       0
Bank Sta=5018.3,5022.3
Exp/Cntr=0.3,0.1

Type RM Length L Ch R = 1,2562,159,159,159
BEGIN DESCRIPTION:
elmc725
END DESCRIPTION:
XS GIS Cut Line= 3
      1501071.22      6764020.08      1501305.57      6764034.40
      1501691.84      6763981.26
#Sta/Elev= 30
  4766.3 2333.36  4770.7 2333.36  4809.6 2323.08  4814.7 2323.02  4820.2 2320.78
  4830.2 2318.49  4880.3 2310.48  4910.3 2307.62  4920.4 2305.88  4940.4 2300.83
  4970.5 2295.43  4976.8 2290.68  4981.8 2290.76  4990.5 2288.22  4996.3 2287.53
  4996.5 2287.03  5000.3 2287.53  5013.5 2287.93  5030.8 2293.28  5040.9 2295.35
  5080.5 2297.12  5182.2 2297.50  5212.5 2295.99  5251.5 2295.42  5263.0 2296.53
  5283.2 2302.73  5301.6 2304.84  5313.4 2307.48  5351.8 2309.79  5391.0 2312.97
#Mann=5,-1,0
  4766.3    0.07       0  4996.3    0.07       0  5000.3    0.07       0
  5251.5   0.035       0  5351.8    0.16       0
Bank Sta=4996.3,5000.3
Exp/Cntr=0.3,0.1

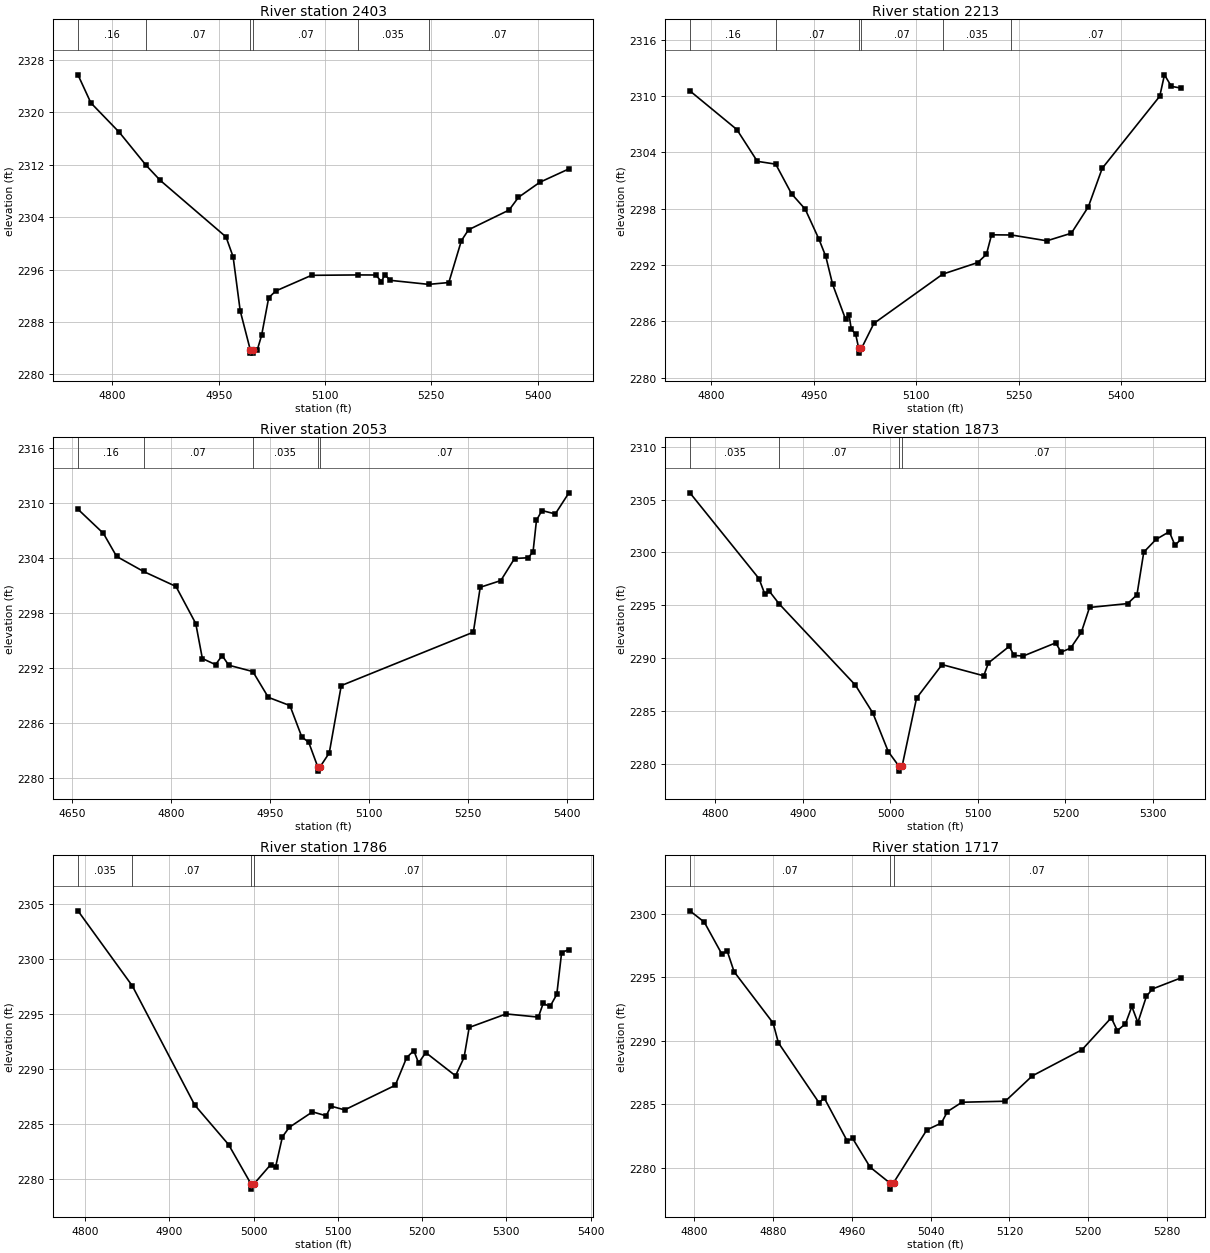
Type RM Length L Ch R = 1,2403,190,190,190
BEGIN DESCRIPTION:
elmc724
END DESCRIPTION:
XS GIS Cut Line= 3
      1501056.86      6764173.73      1501305.57      6764193.26
      1501745.72      6764143.77
#Sta/Elev= 30
  4751.6 2325.72  4769.8 2321.44  4809.9 2316.95  4847.8 2311.90  4867.6 2309.62
  4960.4 2300.99  4970.4 2297.96  4980.4 2289.72  4994.6 2283.76  4994.9 2283.26
  4998.4 2283.26  4998.6 2283.76  5004.5 2283.76  5010.6 2285.98  5020.6 2291.72
  5030.7 2292.75  5081.0 2295.13  5146.1 2295.19  5171.6 2295.18  5179.5 2294.18
  5184.5 2295.23  5191.7 2294.37  5246.1 2293.75  5274.6 2294.03  5292.3 2300.41
  5302.4 2302.08  5359.6 2305.09  5372.8 2307.03  5403.0 2309.33  5444.0 2311.37
#Mann=6,-1,0
  4751.6    0.16       0  4847.8    0.07       0  4994.6    0.07       0
  4998.6    0.07       0  5146.1   0.035       0  5246.1    0.07       0
Bank Sta=4994.6,4998.6
Exp/Cntr=0.3,0.1

Type RM Length L Ch R = 1,2213,160,160,160
BEGIN DESCRIPTION:
elmc723
END DESCRIPTION:
XS GIS Cut Line= 3
      1501076.43      6764370.34      1501314.68      6764383.36
      1501788.69      6764307.83
#Sta/Elev= 30
  4768.5 2310.56  4837.2 2306.44  4867.2 2303.05  4894.1 2302.75  4917.3 2299.59
  4937.3 2297.95  4957.4 2294.75  4967.4 2292.91  4977.4 2289.94  4996.4 2286.21
  5001.5 2286.64  5004.8 2285.13  5011.0 2284.66  5015.6 2283.11  5015.8 2282.61
  5019.6 2283.11  5037.8 2285.78  5138.6 2291.03  5189.7 2292.26  5202.5 2293.14
  5210.0 2295.22  5239.2 2295.20  5291.0 2294.58  5326.8 2295.39  5351.7 2298.21
  5372.0 2302.31  5456.2 2309.99  5463.1 2312.27  5473.2 2311.04  5487.1 2310.86
#Mann=6,-1,0
  4768.5    0.16       0  4894.1    0.07       0  5015.6    0.07       0
  5019.6    0.07       0  5138.6   0.035       0  5239.2    0.07       0
Bank Sta=5015.6,5019.6
Exp/Cntr=0.3,0.1

Type RM Length L Ch R = 1,2053,180,180,180
BEGIN DESCRIPTION:
elmc722
END DESCRIPTION:
XS GIS Cut Line= 3
      1501076.42      6764512.27      1501395.41      6764505.76
      1501804.29      6764388.56
#Sta/Elev= 30
  4658.5 2309.31  4697.1 2306.68  4717.1 2304.17  4758.0 2302.53  4807.1 2300.90
  4837.1 2296.86  4847.1 2293.05  4867.1 2292.38  4877.1 2293.37  4887.1 2292.32
  4923.6 2291.63  4947.1 2288.82  4979.9 2287.92  4997.9 2284.50  5008.3 2283.93
  5021.9 2281.28  5022.1 2280.78  5025.9 2281.28  5039.5 2282.76  5057.7 2290.10
  5258.0 2295.92  5268.4 2300.81  5299.6 2301.54  5320.4 2303.94  5341.2 2304.03
  5348.5 2304.68  5353.7 2308.12  5362.0 2309.17  5382.2 2308.80  5402.9 2311.10
#Mann=5,-1,0
  4658.5    0.16       0  4758.0    0.07       0  4923.6   0.035       0
  5021.9   0.035       0  5025.9    0.07       0
Bank Sta=5021.9,5025.9
Exp/Cntr=0.3,0.1

Type RM Length L Ch R = 1,1873,87,87,87
BEGIN DESCRIPTION:
elmc365
END DESCRIPTION:
XS GIS Cut Line= 3
      1501226.17      6764677.63      1501455.05      6764665.52
      1501761.29      6764537.56
#Sta/Elev= 30
  4770.8 2305.64  4849.7 2297.52  4856.6 2296.01  4861.6 2296.32  4872.7 2295.13
  4959.9 2287.43  4979.9 2284.78  4997.5 2281.13  5009.4 2279.78  5009.6 2279.28
  5013.4 2279.78  5029.8 2286.19  5059.0 2289.37  5106.6 2288.31  5112.0 2289.53
  5135.8 2291.10  5141.2 2290.24  5151.7 2290.18  5188.9 2291.43  5195.0 2290.55
  5205.9 2290.93  5218.1 2292.42  5227.5 2294.78  5271.1 2295.15  5281.7 2295.98
  5289.5 2300.02  5303.4 2301.22  5318.7 2301.96  5325.1 2300.68  5331.9 2301.22
#Mann=4,-1,0
  4770.8   0.035       0  4872.7    0.07       0  5009.4    0.07       0
  5013.4    0.07       0
Bank Sta=5009.4,5013.4
Exp/Cntr=0.3,0.1

Type RM Length L Ch R = 1,1786,69,69,69
BEGIN DESCRIPTION:
elmc721
END DESCRIPTION:
XS GIS Cut Line= 3
      1501247.00      6764772.68      1501456.61      6764753.15
      1501784.77      6764577.35
#Sta/Elev= 30
  4791.4 2304.42  4856.0 2297.58  4930.0 2286.75  4970.2 2283.15  4996.6 2279.60
  4996.8 2279.10  5000.6 2279.60  5020.3 2281.34  5025.9 2281.09  5034.1 2283.86
  5042.2 2284.72  5069.8 2286.13  5086.1 2285.77  5091.7 2286.65  5108.0 2286.31
  5168.1 2288.55  5181.6 2291.07  5190.1 2291.70  5195.7 2290.58  5204.3 2291.52
  5239.6 2289.41  5249.7 2291.08  5255.8 2293.81  5299.7 2295.04  5337.9 2294.75
  5343.6 2295.99  5351.8 2295.72  5359.8 2296.82  5365.5 2300.62  5374.2 2300.90
#Mann=4,-1,0
  4791.4   0.035       0  4856.0    0.07       0  4996.6    0.07       0
  5000.6    0.07       0
Bank Sta=4996.6,5000.6
Exp/Cntr=0.3,0.1

Type RM Length L Ch R = 1,1717,81,81,81
BEGIN DESCRIPTION:
elmc718
END DESCRIPTION:
XS GIS Cut Line= 3
      1501293.89      6764897.67      1501473.54      6764818.26
      1501721.08      6764644.59
#Sta/Elev= 30
  4795.4 2300.24  4810.0 2299.35  4827.8 2296.84  4833.3 2297.07  4840.3 2295.44
  4879.9 2291.40  4885.3 2289.84  4926.5 2285.12  4931.9 2285.48  4955.2 2282.10
  4960.7 2282.30  4978.5 2280.03  4998.3 2278.80  4998.6 2278.30  5002.3 2278.80
  5036.1 2282.97  5050.9 2283.51  5057.0 2284.41  5071.8 2285.15  5115.8 2285.23
  5143.3 2287.23  5193.8 2289.29  5223.5 2291.81  5229.6 2290.80  5237.9 2291.33
  5244.4 2292.70  5250.5 2291.43  5259.2 2293.50  5265.3 2294.08  5294.2 2294.95
#Mann=3,-1,0
  4795.4    0.07       0  4998.3    0.07       0  5002.3    0.07       0
Bank Sta=4998.3,5002.3
Exp/Cntr=0.3,0.1

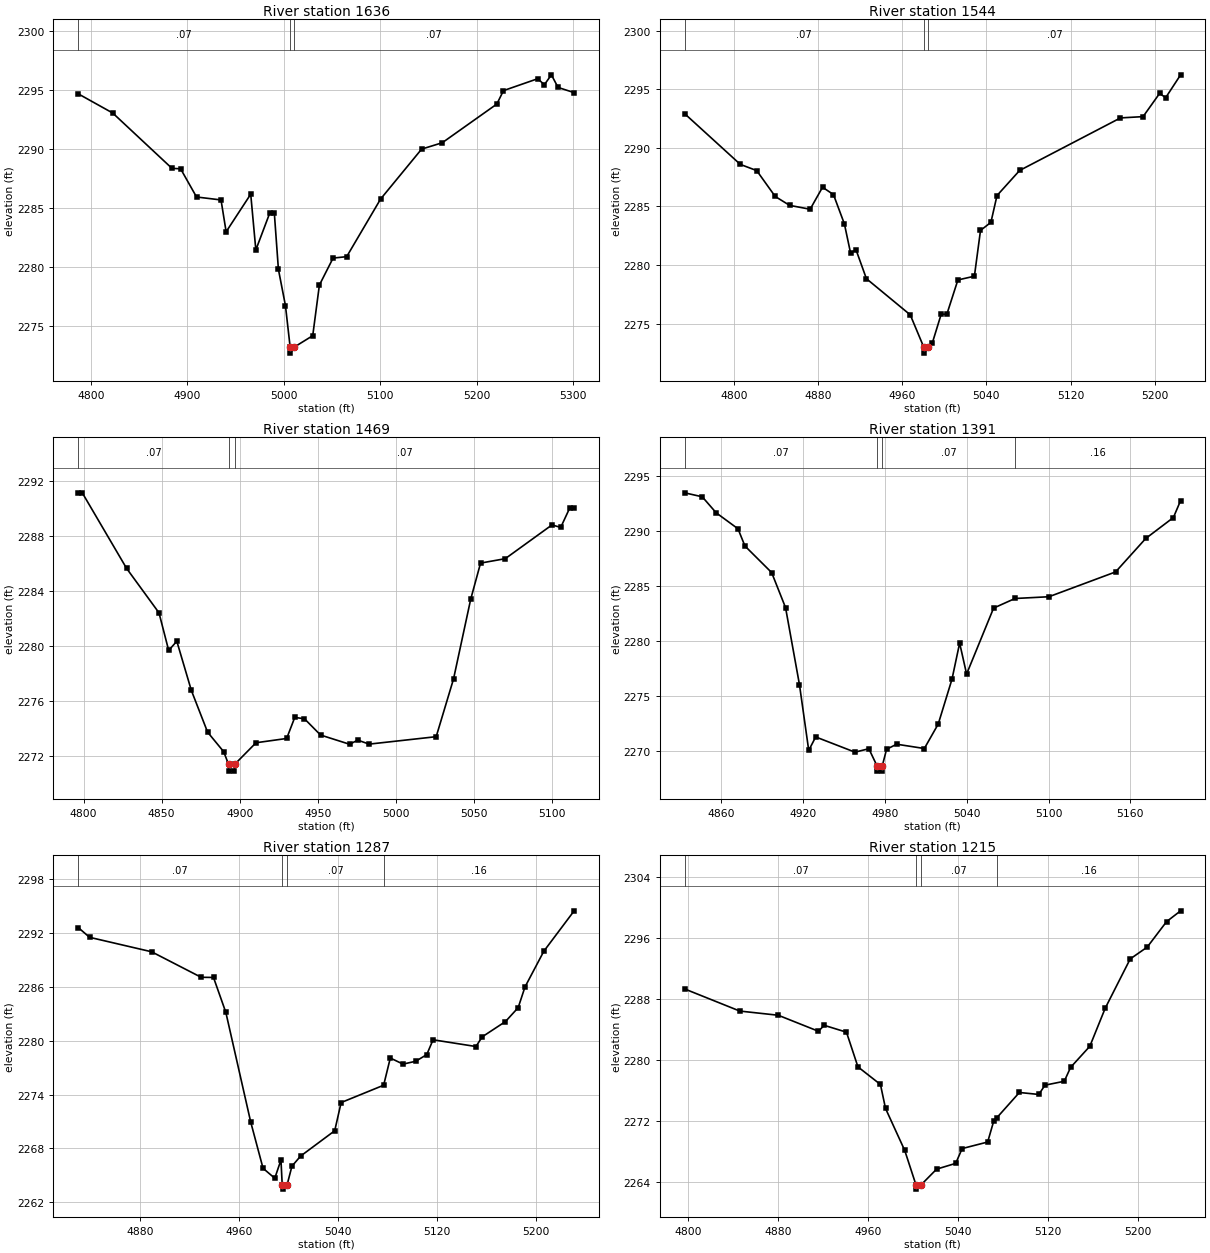
Type RM Length L Ch R = 1,1636,92,92,92
BEGIN DESCRIPTION:
elmc720
END DESCRIPTION:
XS GIS Cut Line= 3
      1501355.06      6764914.61      1501543.85      6764846.90
      1501770.20      6764629.66
#Sta/Elev= 30
  4786.8 2294.68  4822.6 2293.05  4884.0 2288.36  4893.0 2288.32  4909.5 2285.93
  4934.9 2285.68  4940.2 2282.98  4965.7 2286.17  4971.0 2281.44  4985.3 2284.54
  4990.2 2284.54  4994.4 2279.80  5001.7 2276.72  5006.6 2273.19  5006.8 2272.69
  5010.6 2273.19  5030.0 2274.17  5036.9 2278.46  5051.1 2280.75  5065.2 2280.87
  5100.4 2285.76  5142.9 2289.99  5164.3 2290.53  5220.9 2293.81  5227.8 2294.95
  5263.3 2295.96  5270.2 2295.45  5277.5 2296.29  5284.4 2295.22  5301.1 2294.78
#Mann=3,-1,0
  4786.8    0.07       0  5006.6    0.07       0  5010.6    0.07       0
Bank Sta=5006.6,5010.6
Exp/Cntr=0.3,0.1

Type RM Length L Ch R = 1,1544,75,75,75
BEGIN DESCRIPTION:
elmc719
END DESCRIPTION:
XS GIS Cut Line= 3
      1501399.35      6764938.04      1501636.30      6764867.74
      1501830.12      6764754.56
#Sta/Elev= 30
  4753.1 2292.92  4806.0 2288.59  4821.6 2288.06  4839.2 2285.85  4852.9 2285.09
  4872.4 2284.76  4884.2 2286.64  4894.6 2286.01  4905.0 2283.50  4910.8 2281.04
  4916.1 2281.28  4925.9 2278.83  4967.6 2275.74  4980.5 2272.97  4980.8 2272.47
  4984.5 2272.97  4988.5 2273.31  4997.0 2275.79  5002.4 2275.79  5012.9 2278.72
  5028.6 2279.04  5034.4 2282.95  5044.3 2283.64  5050.1 2285.93  5071.6 2288.07
  5167.5 2292.56  5189.0 2292.67  5204.7 2294.65  5210.5 2294.29  5224.7 2296.24
#Mann=3,-1,0
  4753.1    0.07       0  4980.5    0.07       0  4984.5    0.07       0
Bank Sta=4980.5,4984.5
Exp/Cntr=0.3,0.1

Type RM Length L Ch R = 1,1469,78,78,78
BEGIN DESCRIPTION:
elmc364
END DESCRIPTION:
XS GIS Cut Line= 3
      1501454.97      6764988.01      1501651.67      6764936.22
      1501754.98      6764888.01
#Sta/Elev= 30
  4796.6 2291.11  4799.2 2291.11  4827.6 2285.62  4848.3 2282.40  4854.5 2279.67
  4859.7 2280.34  4869.0 2276.77  4879.4 2273.74  4889.7 2272.32  4892.8 2271.41
  4893.1 2270.91  4896.6 2270.91  4896.8 2271.41  4910.4 2272.97  4930.0 2273.28
  4935.2 2274.81  4941.4 2274.71  4951.7 2273.53  4970.3 2272.86  4975.5 2273.16
  4982.8 2272.87  5025.7 2273.41  5036.8 2277.60  5047.8 2283.39  5054.1 2286.01
  5069.9 2286.33  5099.8 2288.78  5105.4 2288.60  5111.3 2290.04  5114.0 2290.04
#Mann=3,-1,0
  4796.6    0.07       0  4892.8    0.07       0  4896.8    0.07       0
Bank Sta=4892.8,4896.8
Exp/Cntr=0.3,0.1

Type RM Length L Ch R = 1,1391,104,104,104
BEGIN DESCRIPTION:
elmc717
END DESCRIPTION:
XS GIS Cut Line= 3
      1501442.31      6765030.49      1501605.05      6764999.25
      1501800.23      6764965.42
#Sta/Elev= 30
  4833.1 2293.44  4846.0 2293.08  4856.2 2291.63  4872.2 2290.18  4877.3 2288.62
  4896.9 2286.21  4907.1 2283.03  4917.3 2276.05  4924.1 2270.09  4929.2 2271.31
  4958.0 2269.93  4968.2 2270.24  4974.1 2268.71  4974.4 2268.21  4977.9 2268.21
  4978.1 2268.71  4981.2 2270.19  4988.6 2270.65  5008.9 2270.26  5019.1 2272.48
  5029.2 2276.55  5034.8 2279.82  5039.9 2277.01  5059.7 2282.99  5075.4 2283.86
  5100.3 2284.02  5149.2 2286.27  5171.3 2289.30  5191.6 2291.20  5196.9 2292.74
#Mann=4,-1,0
  4833.1    0.07       0  4974.1    0.07       0  4978.1    0.07       0
  5075.4    0.16       0
Bank Sta=4974.1,4978.1
Exp/Cntr=0.3,0.1

Type RM Length L Ch R = 1,1287,72,72,72
BEGIN DESCRIPTION:
elmc716
END DESCRIPTION:
XS GIS Cut Line= 3
      1501435.78      6765091.70      1501605.05      6765103.41
      1501828.67      6765042.66
#Sta/Elev= 30
  4829.6 2292.60  4838.8 2291.51  4889.0 2289.90  4929.1 2287.06  4939.1 2287.04
  4949.1 2283.14  4969.2 2270.95  4979.2 2265.79  4988.7 2264.68  4993.7 2266.72
  4994.7 2263.97  4995.0 2263.47  4998.7 2263.97  5002.6 2266.03  5009.6 2267.15
  5037.2 2269.97  5042.4 2273.11  5076.8 2275.04  5082.2 2278.07  5092.5 2277.39
  5102.8 2277.71  5111.7 2278.45  5116.8 2280.10  5151.5 2279.35  5156.6 2280.43
  5175.4 2282.13  5185.7 2283.68  5191.2 2285.98  5206.5 2289.97  5231.0 2294.46
#Mann=4,-1,0
  4829.6    0.07       0  4994.7    0.07       0  4998.7    0.07       0
  5076.8    0.16       0
Bank Sta=4994.7,4998.7
Exp/Cntr=0.3,0.1

Type RM Length L Ch R = 1,1215,97,97,97
BEGIN DESCRIPTION:
elmc715
END DESCRIPTION:
XS GIS Cut Line= 3
      1501452.67      6765180.24      1501621.98      6765155.50
      1501865.50      6765039.60
#Sta/Elev= 30
  4796.9 2289.34  4845.9 2286.44  4880.1 2285.89  4915.8 2283.79  4920.9 2284.57
  4940.7 2283.67  4950.9 2279.12  4970.9 2276.81  4975.4 2273.67  4992.5 2268.15
  5002.6 2263.58  5002.8 2263.08  5006.6 2263.58  5020.8 2265.70  5037.8 2266.46
  5043.5 2268.40  5066.2 2269.26  5071.7 2272.07  5074.2 2272.42  5094.4 2275.76
  5111.6 2275.50  5117.2 2276.72  5134.3 2277.23  5139.9 2279.05  5157.0 2281.82
  5170.7 2286.82  5192.9 2293.28  5208.0 2294.83  5225.2 2298.17  5237.7 2299.59
#Mann=4,-1,0
  4796.9    0.07       0  5002.6    0.07       0  5006.6    0.07       0
  5074.2    0.16       0
Bank Sta=5002.6,5006.6
Exp/Cntr=0.3,0.1