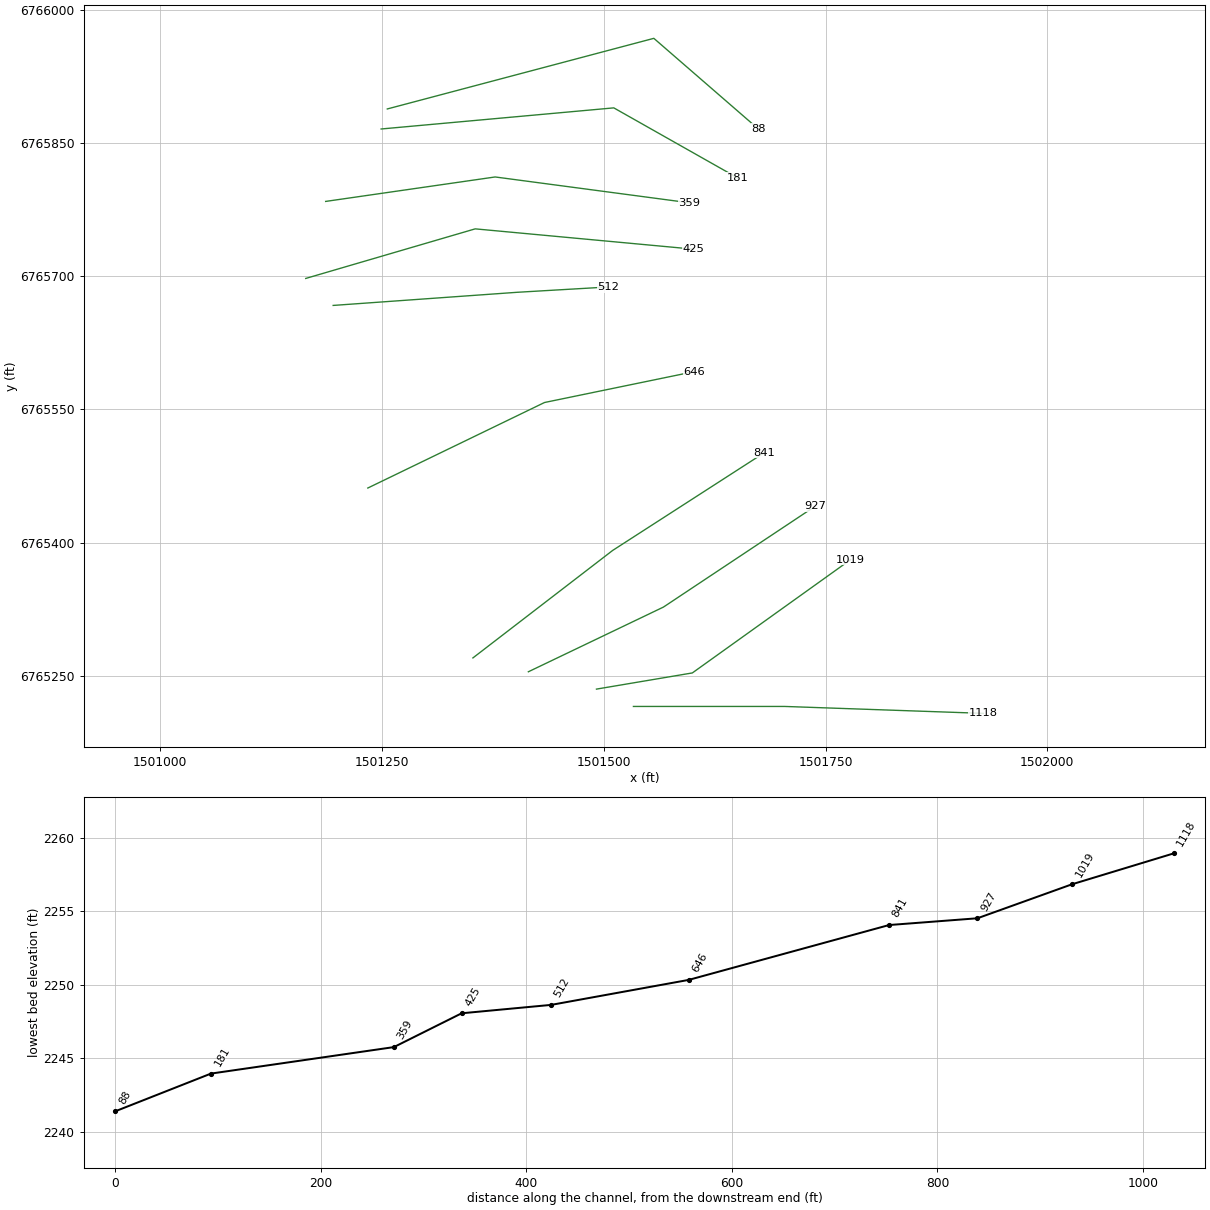
HEC-RAS study Elm 35.prj: Elm 35 Base Level Engineering

--- Elm 35.g01 (geometry) --- (continued)

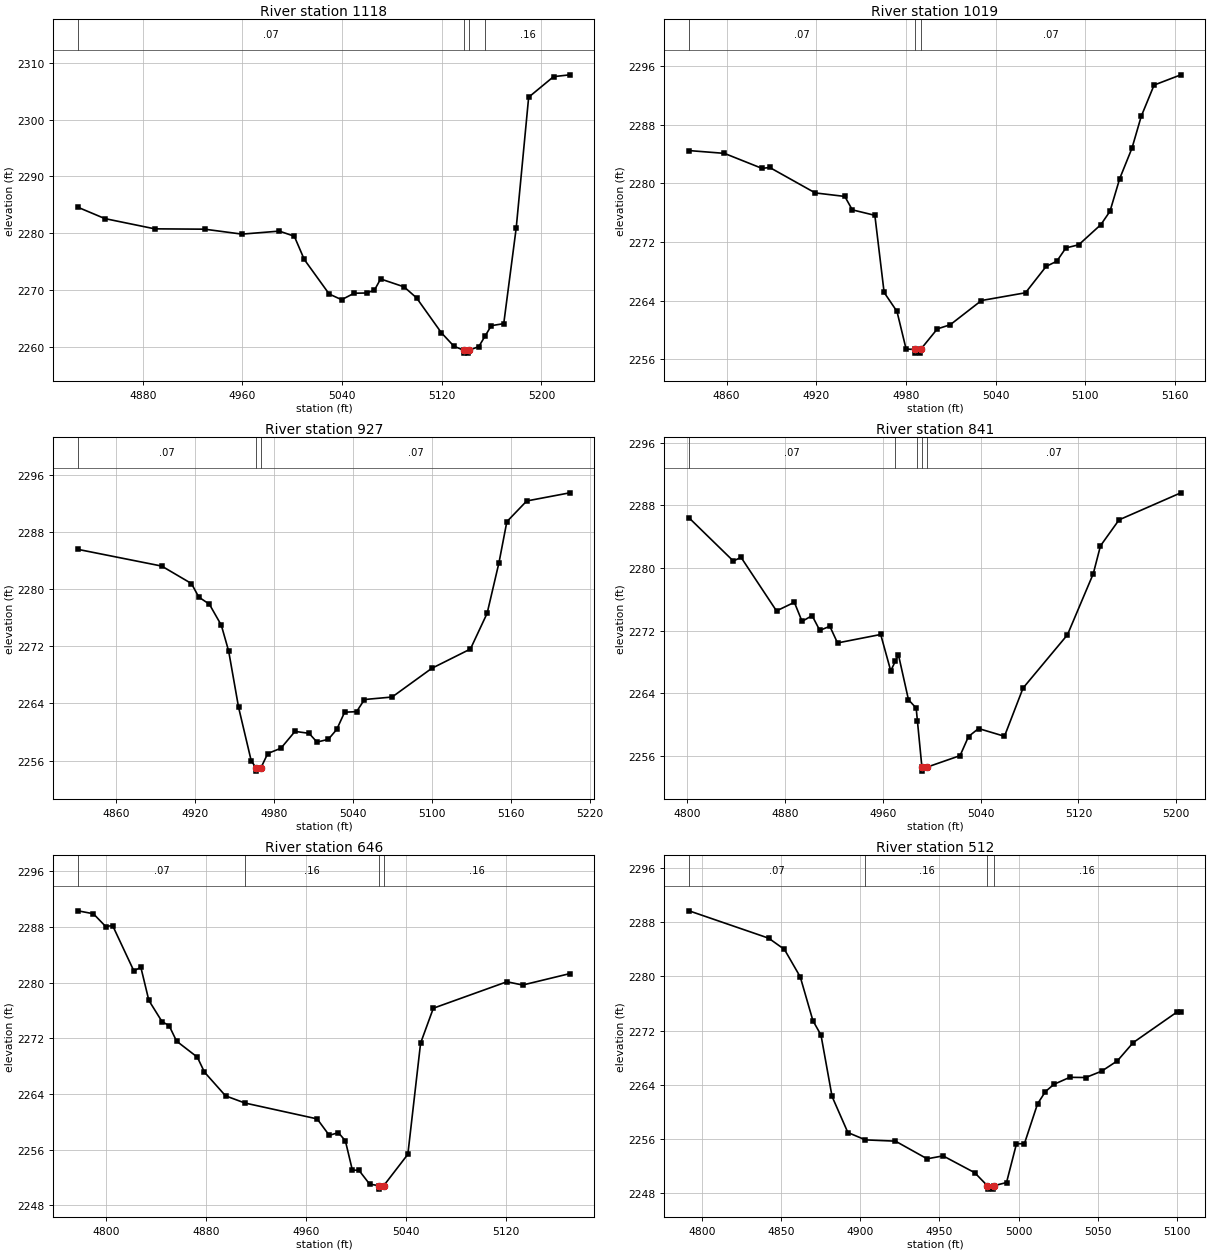
Type RM Length L Ch R = 1,1118,99,99,99
BEGIN DESCRIPTION:
elmc712
END DESCRIPTION:
XS GIS Cut Line= 3
      1501533.41      6765215.39      1501704.01      6765215.39
      1501927.97      6765207.58
#Sta/Elev= 30
  4828.0 2284.58  4849.6 2282.59  4889.6 2280.79  4929.6 2280.73  4959.6 2279.86
  4989.6 2280.39  5001.6 2279.49  5009.6 2275.40  5029.6 2269.32  5039.6 2268.32
  5049.6 2269.46  5059.6 2269.50  5065.9 2270.00  5070.9 2271.97  5089.7 2270.58
  5099.7 2268.65  5119.7 2262.49  5129.7 2260.14  5137.7 2259.42  5137.9 2258.92
  5141.4 2258.92  5141.7 2259.42  5149.7 2260.07  5154.7 2261.91  5159.7 2263.75
  5169.7 2264.11  5179.7 2280.92  5189.7 2303.95  5209.7 2307.57  5222.7 2307.89
#Mann=4,-1,0
  4828.0    0.07       0  5137.7    0.07       0  5141.7    0.07       0
  5154.7    0.16       0
Bank Sta=5137.7,5141.7
Exp/Cntr=0.3,0.1

Type RM Length L Ch R = 1,1019,92,92,92
BEGIN DESCRIPTION:
elmc713
END DESCRIPTION:
XS GIS Cut Line= 3
      1501491.73      6765234.92      1501599.84      6765253.15
      1501778.26      6765380.78
#Sta/Elev= 30
  4834.9 2284.47  4858.5 2284.09  4883.7 2282.04  4888.9 2282.16  4919.3 2278.69
  4939.1 2278.21  4944.1 2276.38  4959.2 2275.63  4965.4 2265.10  4974.0 2262.51
  4980.1 2257.38  4985.8 2257.32  4986.0 2256.82  4989.5 2256.82  4989.8 2257.32
  5001.0 2260.13  5009.6 2260.69  5030.5 2264.00  5060.0 2265.06  5073.8 2268.66
  5080.9 2269.36  5087.0 2271.18  5095.6 2271.61  5110.4 2274.36  5116.5 2276.18
  5123.0 2280.64  5131.2 2284.79  5137.4 2289.14  5146.0 2293.41  5163.9 2294.81
#Mann=3,-1,0
  4834.9    0.07       0  4985.8    0.07       0  4989.8    0.07       0
Bank Sta=4985.8,4989.8
Exp/Cntr=0.3,0.1

Type RM Length L Ch R = 1,927,86,86,86
BEGIN DESCRIPTION:
elmc714
END DESCRIPTION:
XS GIS Cut Line= 3
      1501414.95      6765254.46      1501567.29      6765327.37
      1501737.90      6765440.68
#Sta/Elev= 30
  4830.9 2285.60  4894.5 2283.26  4917.1 2280.81  4922.7 2278.91  4930.7 2277.92
  4939.8 2274.97  4945.4 2271.33  4952.9 2263.47  4962.5 2255.98  4966.0 2255.01
  4966.3 2254.51  4970.0 2255.01  4975.1 2256.98  4985.1 2257.72  4995.8 2260.08
  5006.5 2259.81  5012.5 2258.58  5021.1 2258.97  5027.5 2260.35  5033.5 2262.77
  5042.6 2262.85  5048.6 2264.55  5069.6 2264.90  5099.7 2268.92  5129.1 2271.63
  5141.8 2276.64  5150.8 2283.74  5156.8 2289.49  5171.9 2292.39  5204.6 2293.53
#Mann=3,-1,0
  4830.9    0.07       0  4966.0    0.07       0  4970.0    0.07       0
Bank Sta=4966,4970
Exp/Cntr=0.3,0.1

Type RM Length L Ch R = 1,841,195,195,195
BEGIN DESCRIPTION:
elmc711
END DESCRIPTION:
XS GIS Cut Line= 3
      1501352.42      6765270.06      1501510.00      6765391.17
      1501680.97      6765501.27
#Sta/Elev= 30
  4801.6 2286.39  4837.8 2280.88  4844.1 2281.35  4873.1 2274.51  4887.7 2275.61
  4894.0 2273.17  4902.2 2273.91  4908.5 2272.02  4916.7 2272.55  4923.0 2270.42
  4958.3 2271.50  4966.5 2266.86  4970.2 2268.06  4972.8 2268.91  4981.0 2263.17
  4987.3 2262.10  4988.3 2260.49  4992.0 2254.55  4992.3 2254.05  4996.0 2254.55
  5023.2 2256.03  5030.1 2258.47  5038.3 2259.49  5059.5 2258.50  5074.7 2264.66
  5111.0 2271.46  5132.1 2279.26  5138.0 2282.82  5153.2 2286.14  5203.7 2289.59
#Mann=5,-1,0
  4801.6    0.07       0  4970.2    0.16       0  4988.3    0.07       0
  4992.0    0.07       0  4996.0    0.07       0
Bank Sta=4992,4996
Exp/Cntr=0.3,0.1

Type RM Length L Ch R = 1,646,134,134,134
BEGIN DESCRIPTION:
elmc710
END DESCRIPTION:
XS GIS Cut Line= 3
      1501233.93      6765461.48      1501433.17      6765557.84
      1501601.91      6765592.62
#Sta/Elev= 30
  4777.3 2290.30  4789.6 2289.88  4799.5 2288.04  4805.0 2288.19  4822.0 2281.67
  4827.6 2282.19  4834.0 2277.43  4844.6 2274.37  4850.2 2273.81  4856.2 2271.58
  4872.8 2269.28  4878.5 2267.13  4895.4 2263.72  4910.9 2262.69  4968.7 2260.41
  4978.4 2258.05  4985.7 2258.43  4991.3 2257.26  4996.9 2253.04  5002.1 2253.04
  5010.7 2251.04  5017.9 2250.82  5018.2 2250.32  5022.0 2250.82  5041.3 2255.32
  5051.5 2271.29  5061.7 2276.31  5120.6 2280.11  5133.2 2279.64  5170.9 2281.28
#Mann=4,-1,0
  4777.3    0.07       0  4910.9    0.16       0  5017.9    0.07       0
  5022.0    0.16       0
Bank Sta=5017.9,5022
Exp/Cntr=0.3,0.1

Type RM Length L Ch R = 1,512,87,87,87
BEGIN DESCRIPTION:
elmc363
END DESCRIPTION:
XS GIS Cut Line= 3
      1501194.84      6765667.21      1501402.62      6765682.03
      1501505.04      6765688.00
#Sta/Elev= 30
  4791.7 2289.64  4842.0 2285.61  4852.0 2283.95  4862.0 2279.90  4870.0 2273.45
  4875.1 2271.33  4882.1 2262.28  4892.1 2256.96  4903.2 2255.88  4922.2 2255.69
  4942.2 2253.09  4952.3 2253.52  4972.3 2251.04  4980.3 2249.12  4980.5 2248.62
  4984.1 2248.62  4984.4 2249.12  4992.4 2249.59  4998.7 2255.31  5003.7 2255.31
  5012.0 2261.18  5017.0 2263.00  5022.4 2264.07  5032.4 2265.10  5042.5 2265.07
  5052.5 2266.00  5062.5 2267.53  5072.5 2270.22  5100.1 2274.71  5102.6 2274.71
#Mann=4,-1,0
  4791.7    0.07       0  4903.2    0.16       0  4980.3    0.07       0
  4984.4    0.16       0
Bank Sta=4980.3,4984.4
Exp/Cntr=0.3,0.1

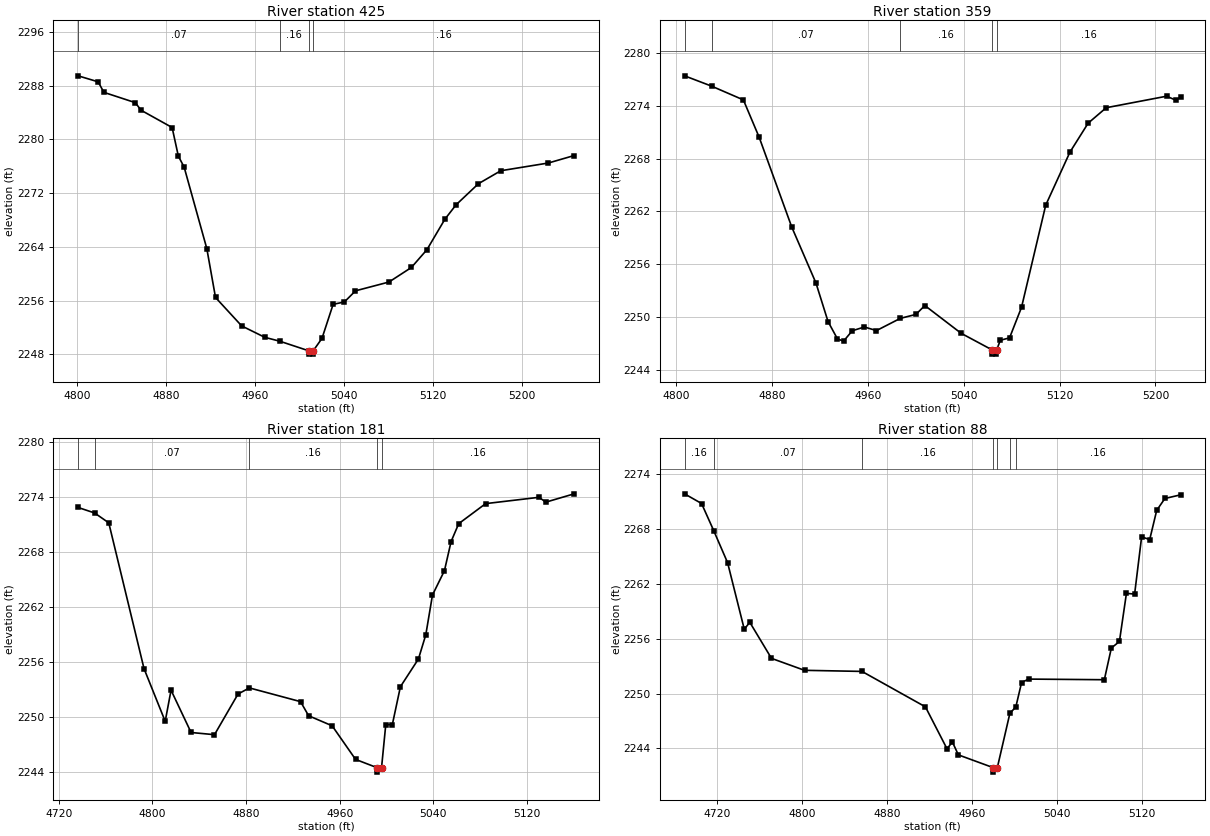
Type RM Length L Ch R = 1,425,66,66,66
BEGIN DESCRIPTION:
elmc763
END DESCRIPTION:
XS GIS Cut Line= 3
      1501163.90      6765697.61      1501355.00      6765753.48
      1501600.65      6765730.65
#Sta/Elev= 30
  4800.9 2289.46  4818.9 2288.57  4824.1 2287.00  4852.3 2285.47  4857.5 2284.34
  4885.4 2281.77  4891.0 2277.51  4896.2 2275.88  4916.6 2263.74  4924.4 2256.48
  4947.9 2252.25  4968.7 2250.55  4982.2 2249.97  5008.1 2248.55  5008.3 2248.05
  5011.9 2248.05  5012.2 2248.55  5020.1 2250.40  5030.1 2255.46  5040.2 2255.81
  5050.2 2257.47  5080.3 2258.78  5100.4 2260.94  5114.4 2263.59  5130.6 2268.14
  5140.6 2270.27  5160.7 2273.41  5180.8 2275.34  5223.6 2276.49  5246.7 2277.60
#Mann=4,-1,0
  4800.9    0.07       0  4982.2    0.16       0  5008.1    0.07       0
  5012.2    0.16       0
Bank Sta=5008.1,5012.2
Exp/Cntr=0.3,0.1

Type RM Length L Ch R = 1,359,178,178,178
BEGIN DESCRIPTION:
elmc762
END DESCRIPTION:
XS GIS Cut Line= 3
      1501186.40      6765784.40      1501377.52      6765811.95
      1501596.59      6765782.84
#Sta/Elev= 30
  4806.9 2277.43  4829.4 2276.26  4856.0 2274.69  4869.2 2270.43  4896.4 2260.21
  4916.6 2253.84  4926.7 2249.45  4934.5 2247.49  4939.6 2247.22  4946.9 2248.41
  4957.0 2248.84  4967.1 2248.43  4987.0 2249.82  5000.0 2250.27  5007.5 2251.28
  5037.8 2248.12  5063.4 2246.25  5063.7 2245.75  5067.3 2245.75  5067.5 2246.25
  5070.5 2247.33  5078.2 2247.60  5088.2 2251.08  5108.4 2262.71  5128.6 2268.74
  5143.8 2272.04  5158.9 2273.80  5209.3 2275.11  5217.1 2274.65  5221.0 2275.02
#Mann=5,-1,0
  4806.9    0.16       0  4829.4    0.07       0  4987.0    0.16       0
  5063.4    0.07       0  5067.5    0.16       0
Bank Sta=5063.4,5067.5
Exp/Cntr=0.3,0.1

Type RM Length L Ch R = 1,181,93,93,93
BEGIN DESCRIPTION:
elmc761
END DESCRIPTION:
XS GIS Cut Line= 3
      1501248.94      6765866.00      1501511.26      6765889.80
      1501650.82      6765810.94
#Sta/Elev= 30
  4736.6 2272.86  4750.7 2272.26  4762.8 2271.18  4792.9 2255.26  4811.0 2249.50
  4816.0 2252.90  4833.1 2248.28  4853.1 2248.04  4873.2 2252.48  4882.9 2253.15
  4926.6 2251.65  4933.5 2250.11  4953.6 2249.01  4973.6 2245.34  4991.7 2244.45
  4991.9 2243.95  4995.8 2244.45  4999.4 2249.14  5005.0 2249.14  5011.9 2253.28
  5027.3 2256.31  5033.6 2258.96  5039.3 2263.30  5049.5 2265.95  5055.2 2269.14
  5061.7 2271.09  5084.7 2273.28  5130.3 2273.97  5136.1 2273.44  5160.3 2274.35
#Mann=5,-1,0
  4736.6    0.16       0  4750.7    0.07       0  4882.9    0.16       0
  4991.7    0.07       0  4995.8    0.16       0
Bank Sta=4991.7,4995.8
Exp/Cntr=0.3,0.1

Type RM Length L Ch R = 1,88,0,0,0
BEGIN DESCRIPTION:
elmc760
END DESCRIPTION:
XS GIS Cut Line= 3
      1501255.88      6765888.57      1501556.42      6765968.14
      1501674.31      6765865.97
#Sta/Elev= 30
  4689.1 2271.87  4705.1 2270.81  4716.5 2267.85  4729.6 2264.33  4745.3 2257.04
  4750.5 2257.80  4770.9 2253.85  4802.0 2252.54  4856.1 2252.42  4915.8 2248.54
  4936.1 2243.95  4941.2 2244.69  4946.8 2243.28  4979.4 2241.89  4979.7 2241.39
  4983.5 2241.89  4995.3 2247.83  5000.9 2248.53  5006.3 2251.20  5012.9 2251.58
  5084.2 2251.51  5090.8 2254.98  5098.4 2255.70  5105.0 2260.97  5112.7 2260.89
  5119.3 2267.16  5126.9 2266.86  5133.5 2270.06  5141.2 2271.36  5156.0 2271.76
#Mann=7,-1,0
  4689.1    0.16       0  4716.5    0.07       0  4856.1    0.16       0
  4979.4    0.07       0  4983.5    0.16       0  4995.3    0.07       0
  5000.9    0.16       0
Bank Sta=4979.4,4983.5
Exp/Cntr=0.3,0.1

Chan Stop Cuts=-1