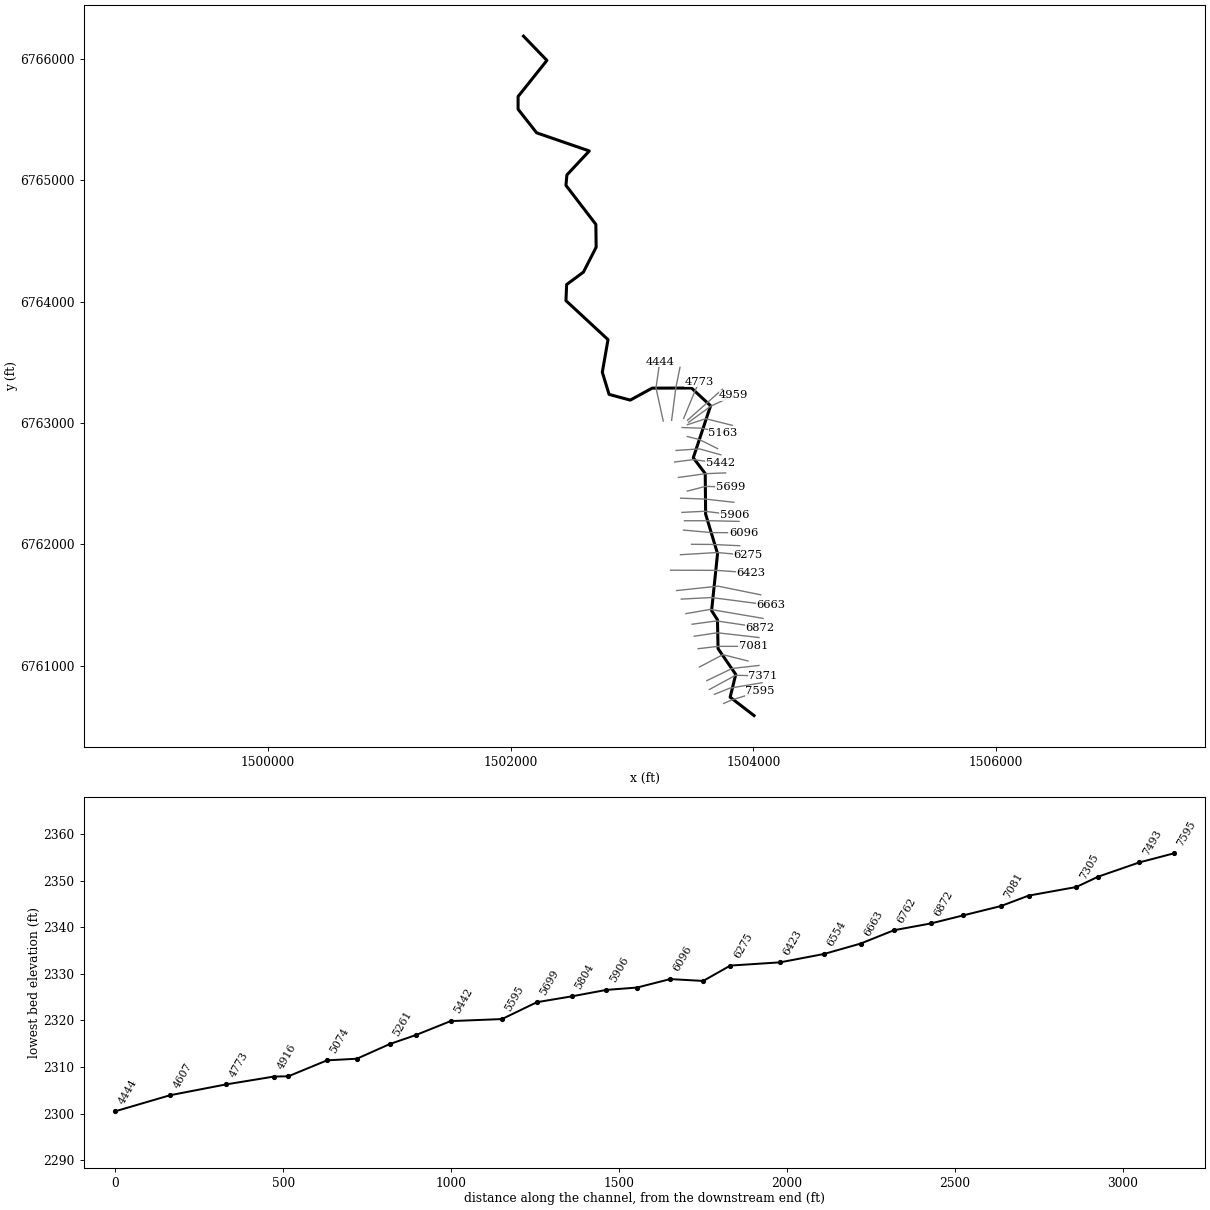
--- Elm 36.prj (project) ---

Proj Title=Elm 36 Base Level Engineering
Current Plan=p01
Default Exp/Contr=0.3,0.1
English Units
Geom File=g01
Flow File=f01
Plan File=p01
BEGIN DESCRIPTION:
Elm 36
END DESCRIPTION:

--- Elm 36.p01 (plan) ---

Plan Title=Multiple Run
Short Identifier=Multiple
Geom File=g01
Flow File=f01
Subcritical Flow
K Sum by GR= 0
Std Step Tol= 0.01
Critical Tol= 0.01
Num of Std Step Trials= 20
Max Error Tol= 0.3
Flow Tol Ratio= 0.001
Split Flow NTrial= 30
Split Flow Tol= 0.02
Split Flow Ratio= 0.02
Log Output Level= 0
Friction Slope Method= 1
Unsteady Friction Slope Method= 2
Unsteady Bridges Friction Slope Method= 1
Parabolic Critical Depth
Global Vel Dist=  1 , 1 , 1
Global Log Level= 0
CheckData=True
Encroach Param= -1, 0, 0, 0
BEGIN DESCRIPTION:
Multiple Run
END DESCRIPTION:

--- Elm 36.f01 (steady flow) ---

Flow Title=Multiple
Number of Profiles=7
Profile Names=10-year,25-year,50-year,1pct_min,100-year,1pct_plu,500-year
River Rch & RM= Elm 36,Reach-1,7595
     339     483     607     472     757    1040    1190
Boundary for River Rch & Prof#=Elm 36,Reach-1,1
Up Type=0
Dn Type=3
Dn Slope=0.005
Boundary for River Rch & Prof#=Elm 36,Reach-1,2
Up Type=0
Dn Type=3
Dn Slope=0.005
Boundary for River Rch & Prof#=Elm 36,Reach-1,3
Up Type=0
Dn Type=3
Dn Slope=0.005
Boundary for River Rch & Prof#=Elm 36,Reach-1,4
Up Type=0
Dn Type=3
Dn Slope=0.005
Boundary for River Rch & Prof#=Elm 36,Reach-1,5
Up Type=0
Dn Type=3
Dn Slope=0.005
Boundary for River Rch & Prof#=Elm 36,Reach-1,6
Up Type=0
Dn Type=3
Dn Slope=0.005
Boundary for River Rch & Prof#=Elm 36,Reach-1,7
Up Type=0
Dn Type=3
Dn Slope=0.005

--- Elm 36.g01 (geometry) ---

Geom Title=Existing Conditions

River Reach=Elm 36,Reach-1
Reach XY= 30
      1504005.00      6760588.00      1503808.45      6760739.48
      1503854.40      6760927.38      1503708.75      6761139.55
      1503703.78      6761377.50      1503655.51      6761453.22
      1503704.48      6761922.78      1503606.22      6762248.50
      1503602.93      6762582.14      1503504.51      6762712.96
      1503647.21      6763141.42      1503489.84      6763287.62
      1503165.50      6763286.80      1502984.97      6763188.04
      1502810.40      6763235.29      1502754.61      6763417.87
      1502801.63      6763686.72      1502454.94      6764007.99
      1502460.45      6764140.46      1502599.41      6764243.61
      1502703.80      6764448.50      1502701.47      6764636.54
      1502454.88      6764958.10      1502462.76      6765044.17
      1502647.53      6765241.62      1502213.34      6765391.16
      1502060.40      6765585.57      1502060.40      6765690.43
      1502297.92      6765988.00      1502105.00      6766188.00

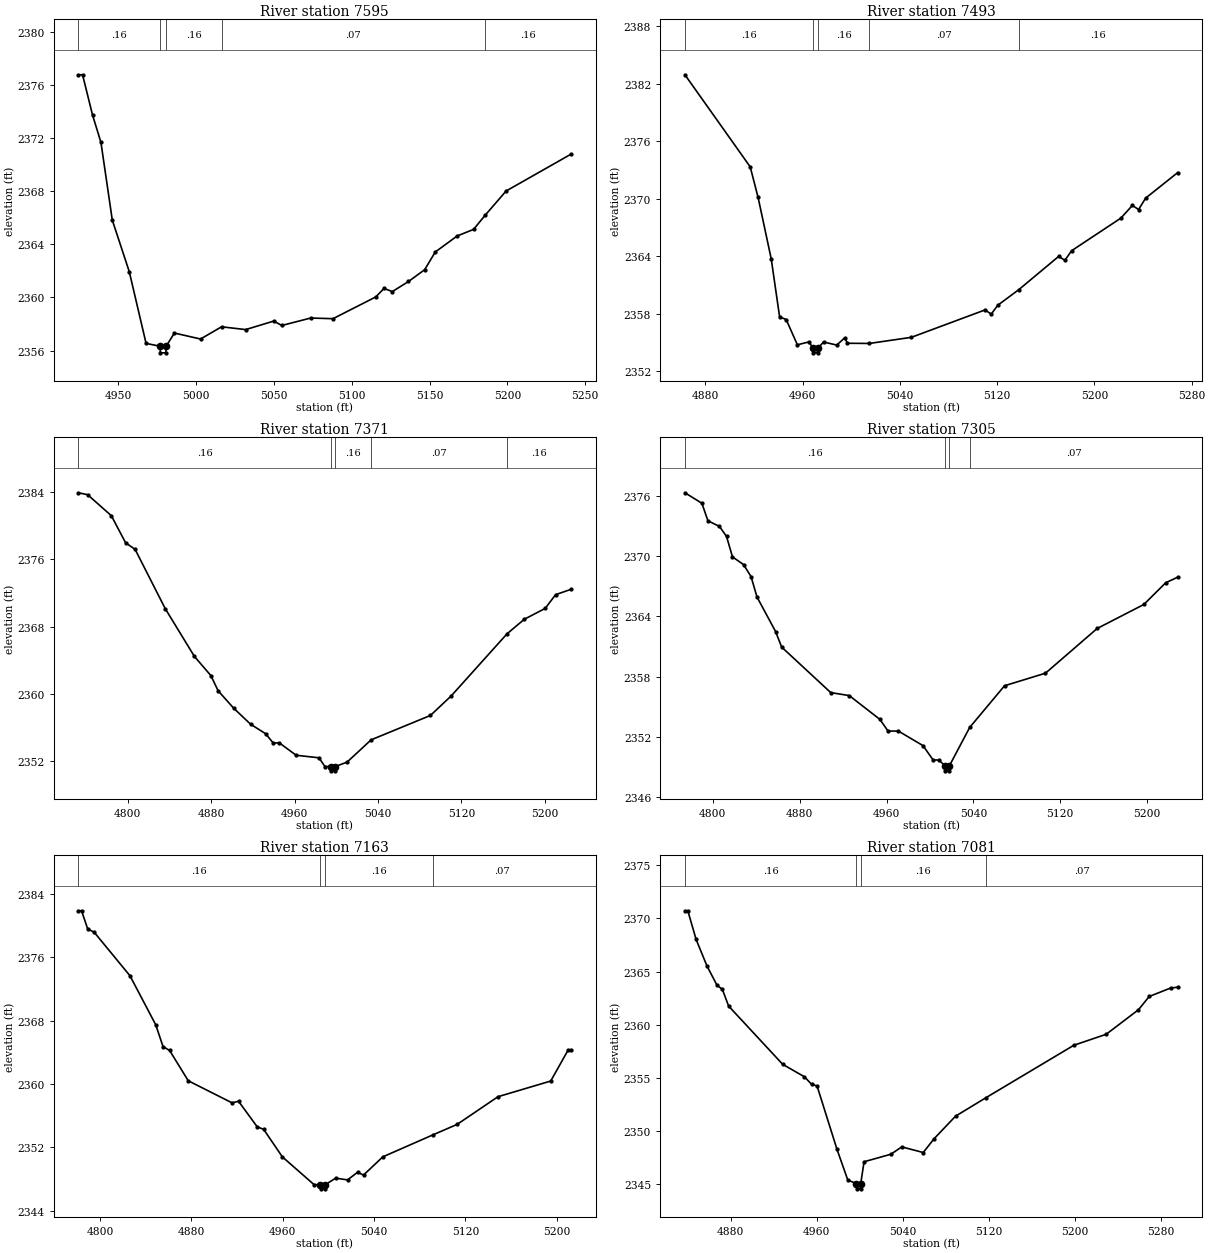
Type RM Length L Ch R = 1,7595,102,102,102
BEGIN DESCRIPTION:
elmc380
END DESCRIPTION:
XS GIS Cut Line= 3
      1503754.98      6760687.99      1503824.56      6760717.80
      1504055.01      6760788.00
#Sta/Elev= 30
  4924.3 2376.76  4927.0 2376.76  4933.4 2373.73  4938.8 2371.67  4946.1 2365.82
  4957.0 2361.94  4967.8 2356.54  4976.7 2356.33  4977.0 2355.83  4980.5 2355.83
  4980.7 2356.33  4986.0 2357.32  5002.8 2356.87  5016.3 2357.79  5031.8 2357.58
  5049.8 2358.22  5055.0 2357.89  5073.6 2358.45  5087.9 2358.40  5115.4 2360.04
  5120.7 2360.68  5126.0 2360.44  5136.4 2361.20  5146.8 2362.09  5153.6 2363.42
  5167.7 2364.63  5178.2 2365.12  5185.6 2366.18  5199.1 2368.01  5240.9 2370.79
#Mann=5,-1,0
  4924.3    0.16       0  4976.7    0.07       0  4980.7    0.16       0
  5016.3    0.07       0  5185.6    0.16       0
Bank Sta=4976.7,4980.7
Exp/Cntr=0.3,0.1

Type RM Length L Ch R = 1,7493,122,122,122
BEGIN DESCRIPTION:
elmc817
END DESCRIPTION:
XS GIS Cut Line= 3
      1503679.18      6760763.29      1503803.75      6760813.55
      1504071.07      6760858.46
#Sta/Elev= 30
  4863.1 2382.93  4916.8 2373.32  4923.3 2370.12  4934.1 2363.71  4941.0 2357.65
  4946.4 2357.38  4955.6 2354.74  4965.1 2355.04  4968.5 2354.40  4968.8 2353.90
  4972.3 2353.90  4972.5 2354.40  4977.2 2355.03  4988.0 2354.71  4994.7 2355.48
  4996.7 2354.90  5014.8 2354.88  5049.4 2355.52  5110.0 2358.38  5115.1 2357.94
  5120.4 2358.86  5137.9 2360.51  5170.6 2363.97  5175.7 2363.56  5181.2 2364.56
  5221.8 2367.97  5231.2 2369.29  5236.3 2368.86  5242.1 2370.05  5268.5 2372.72
#Mann=5,-1,0
  4863.1    0.16       0  4968.5    0.07       0  4972.5    0.16       0
  5014.8    0.07       0  5137.9    0.16       0
Bank Sta=4968.5,4972.5
Exp/Cntr=0.3,0.1

Type RM Length L Ch R = 1,7371,66,66,66
BEGIN DESCRIPTION:
elmc816
END DESCRIPTION:
XS GIS Cut Line= 3
      1503637.18      6760803.07      1503853.31      6760920.25
      1504079.86      6760913.74
#Sta/Elev= 30
  4752.7 2383.88  4761.6 2383.65  4784.3 2381.16  4798.0 2377.94  4807.1 2377.16
  4836.0 2370.12  4864.0 2364.44  4879.7 2362.18  4886.7 2360.37  4901.6 2358.30
  4917.8 2356.40  4932.2 2355.27  4939.6 2354.16  4945.3 2354.19  4961.5 2352.71
  4983.4 2352.41  4989.1 2351.37  4994.7 2351.36  4994.9 2350.86  4998.4 2350.86
  4998.7 2351.36  5010.3 2351.89  5033.4 2354.54  5090.3 2357.44  5110.3 2359.77
  5163.7 2367.13  5180.3 2368.86  5200.3 2370.15  5210.3 2371.78  5225.2 2372.42
#Mann=5,-1,0
  4752.7    0.16       0  4994.7    0.07       0  4998.7    0.16       0
  5033.4    0.07       0  5163.7    0.16       0
Bank Sta=4994.7,4998.7
Exp/Cntr=0.3,0.1

Type RM Length L Ch R = 1,7305,142,142,142
BEGIN DESCRIPTION:
elmc815
END DESCRIPTION:
XS GIS Cut Line= 3
      1503616.38      6760876.00      1503824.67      6760976.24
      1504046.04      6761000.99
#Sta/Elev= 30
  4774.3 2376.30  4789.9 2375.26  4795.5 2373.51  4806.1 2372.95  4812.6 2371.96
  4818.1 2369.92  4828.3 2369.15  4835.2 2367.96  4840.7 2365.92  4857.8 2362.49
  4863.4 2360.94  4908.6 2356.41  4925.7 2356.11  4953.9 2353.74  4961.4 2352.58
  4970.9 2352.58  4993.6 2351.13  5002.9 2349.70  5008.1 2349.70  5013.9 2349.12
  5014.1 2348.62  5017.6 2348.62  5017.9 2349.12  5036.6 2352.94  5068.7 2357.09
  5106.4 2358.34  5154.0 2362.79  5197.0 2365.18  5217.1 2367.34  5228.2 2367.90
#Mann=4,-1,0
  4774.3    0.16       0  5013.9    0.07       0  5017.9    0.16       0
  5036.6    0.07       0
Bank Sta=5013.9,5017.9
Exp/Cntr=0.3,0.1

Type RM Length L Ch R = 1,7163,82,82,82
BEGIN DESCRIPTION:
elmc379
END DESCRIPTION:
XS GIS Cut Line= 3
      1503555.03      6760988.02      1503748.86      6761090.17
      1503954.96      6761038.01
#Sta/Elev= 30
  4780.9 2381.90  4783.7 2381.90  4789.1 2379.59  4794.7 2379.20  4826.1 2373.69
  4848.7 2367.49  4855.1 2364.73  4860.8 2364.26  4877.2 2360.42  4915.6 2357.63
  4921.2 2357.84  4937.6 2354.60  4943.2 2354.29  4959.6 2350.81  4987.3 2347.31
  4993.0 2347.27  4993.2 2346.77  4996.7 2346.77  4997.0 2347.27  5006.3 2348.12
  5016.7 2347.90  5025.5 2348.86  5030.7 2348.51  5047.6 2350.81  5091.2 2353.57
  5112.7 2354.91  5148.5 2358.41  5194.7 2360.39  5210.1 2364.34  5212.6 2364.34
#Mann=4,-1,0
  4780.9    0.16       0  4993.0    0.07       0  4997.0    0.16       0
  5091.2    0.07       0
Bank Sta=4993,4997
Exp/Cntr=0.3,0.1

Type RM Length L Ch R = 1,7081,112,112,112
BEGIN DESCRIPTION:
elmc814
END DESCRIPTION:
XS GIS Cut Line= 3
      1503544.68      6761139.00      1503710.08      6761158.54
      1504001.53      6761158.54
#Sta/Elev= 30
  4837.5 2370.72  4840.2 2370.72  4847.9 2368.02  4858.0 2365.52  4867.3 2363.71
  4872.3 2363.32  4878.1 2361.75  4928.4 2356.26  4948.6 2355.09  4955.2 2354.38
  4960.3 2354.23  4978.8 2348.27  4988.9 2345.36  4996.9 2345.04  4997.2 2344.54
  5000.7 2344.54  5000.9 2345.04  5004.0 2347.09  5029.0 2347.80  5039.0 2348.49
  5059.0 2347.96  5069.0 2349.25  5089.0 2351.38  5117.1 2353.11  5199.0 2358.06
  5229.0 2359.09  5259.0 2361.40  5269.0 2362.65  5289.0 2363.45  5295.5 2363.52
#Mann=4,-1,0
  4837.5    0.16       0  4996.9    0.07       0  5000.9    0.16       0
  5117.1    0.07       0
Bank Sta=4996.9,5000.9
Exp/Cntr=0.3,0.1

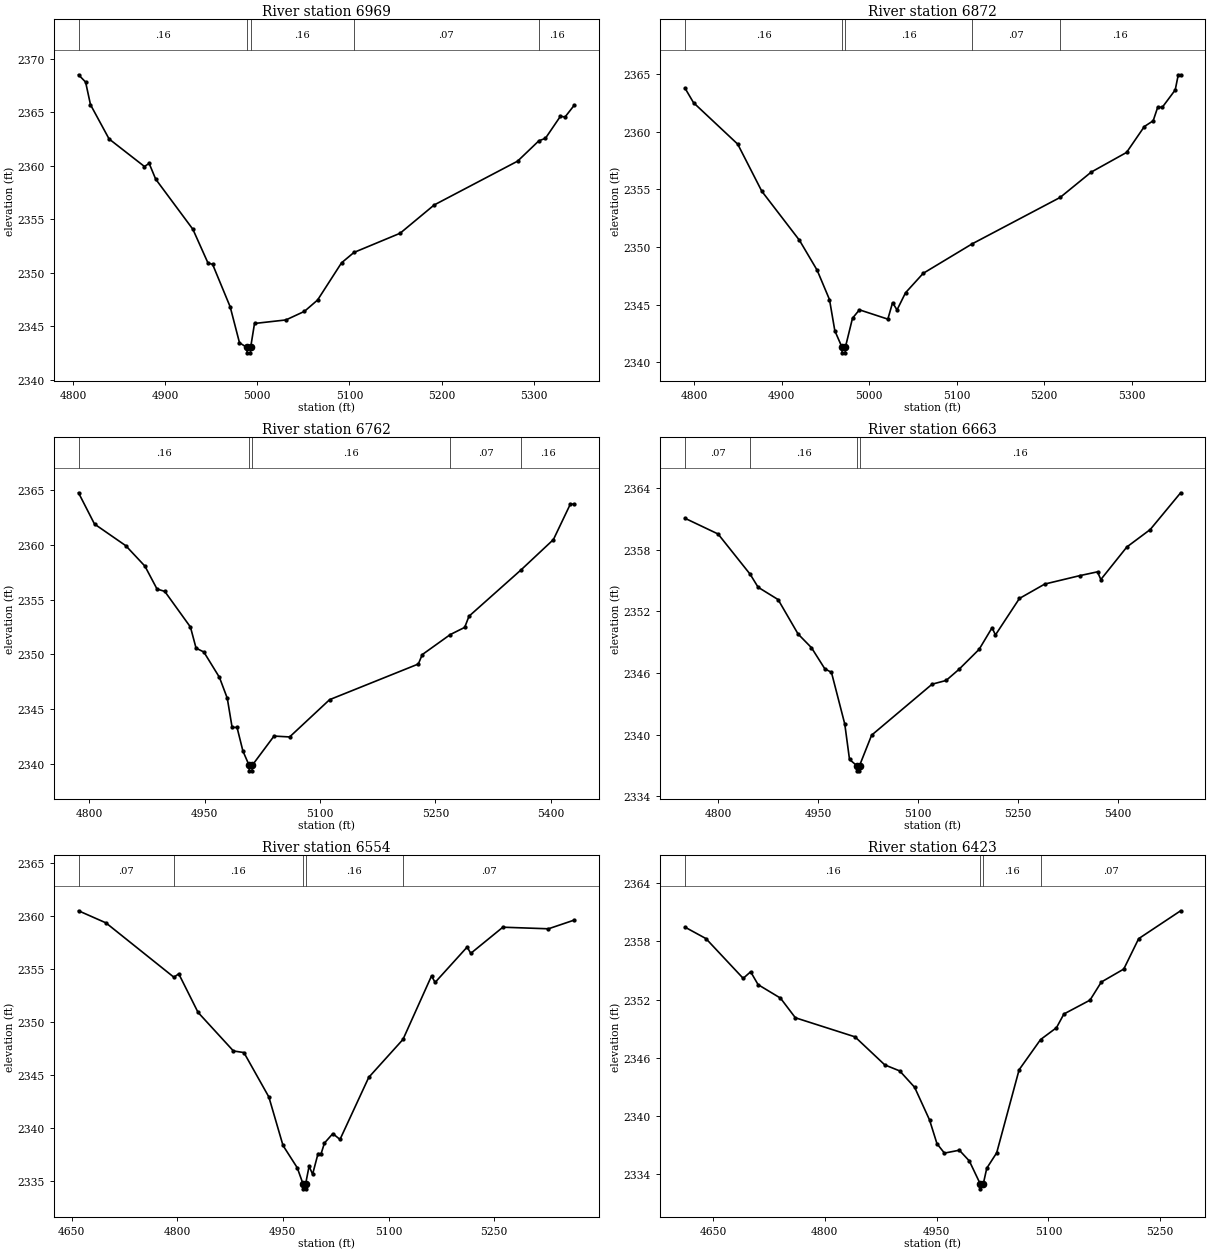
Type RM Length L Ch R = 1,6969,97,97,97
BEGIN DESCRIPTION:
elmc813
END DESCRIPTION:
XS GIS Cut Line= 3
      1503512.18      6761241.87      1503702.27      6761270.51
      1504046.02      6761231.45
#Sta/Elev= 30
  4805.8 2368.49  4813.5 2367.81  4818.8 2365.70  4839.0 2362.50  4877.4 2359.93
  4882.5 2360.22  4889.6 2358.75  4930.0 2354.07  4946.4 2350.92  4951.4 2350.80
  4970.5 2346.83  4980.6 2343.48  4988.7 2343.04  4988.9 2342.54  4992.4 2342.54
  4992.7 2343.04  4996.9 2345.28  5031.0 2345.61  5051.1 2346.41  5065.4 2347.47
  5091.4 2350.94  5104.9 2351.91  5155.0 2353.70  5192.0 2356.34  5282.6 2360.43
  5305.7 2362.33  5312.8 2362.56  5329.1 2364.62  5334.1 2364.55  5344.0 2365.64
#Mann=5,-1,0
  4805.8    0.16       0  4988.7    0.07       0  4992.7    0.16       0
  5104.9    0.07       0  5305.7    0.16       0
Bank Sta=4988.7,4992.7
Exp/Cntr=0.3,0.1

Type RM Length L Ch R = 1,6872,110,110,110
BEGIN DESCRIPTION:
elmc812
END DESCRIPTION:
XS GIS Cut Line= 4
      1503495.27      6761340.83      1503695.76      6761368.17
      1504030.40      6761318.69      1504055.17      6761310.87
#Sta/Elev= 30
  4789.5 2363.81  4799.3 2362.54  4849.8 2358.94  4877.3 2354.85  4920.4 2350.58
  4940.6 2347.98  4954.7 2345.43  4960.8 2342.72  4968.9 2341.30  4969.1 2340.80
  4972.6 2340.80  4972.9 2341.30  4981.0 2343.81  4988.9 2344.54  5021.4 2343.73
  5026.8 2345.16  5031.9 2344.53  5041.6 2346.02  5061.8 2347.71  5117.7 2350.27
  5218.4 2354.31  5253.9 2356.51  5294.3 2358.22  5314.6 2360.47  5324.7 2360.97
  5329.9 2362.15  5335.2 2362.15  5349.9 2363.65  5353.4 2364.97  5356.1 2364.97
#Mann=5,-1,0
  4789.5    0.16       0  4968.9    0.07       0  4972.9    0.16       0
  5117.7    0.07       0  5218.4    0.16       0
Bank Sta=4968.9,4972.9
Exp/Cntr=0.3,0.1

Type RM Length L Ch R = 1,6762,99,99,99
BEGIN DESCRIPTION:
elmc811
END DESCRIPTION:
XS GIS Cut Line= 3
      1503444.47      6761428.07      1503643.68      6761463.22
      1504079.83      6761389.01
#Sta/Elev= 30
  4785.8 2364.77  4806.6 2361.91  4847.3 2359.93  4872.2 2358.06  4887.9 2355.97
  4898.0 2355.75  4931.4 2352.49  4938.7 2350.56  4948.8 2350.21  4969.1 2347.89
  4979.3 2345.98  4985.6 2343.31  4992.0 2343.31  4999.6 2341.16  5007.7 2339.84
  5008.0 2339.34  5011.5 2339.34  5011.7 2339.84  5040.1 2342.52  5060.4 2342.44
  5112.4 2345.85  5227.8 2349.11  5232.9 2349.97  5269.3 2351.80  5288.1 2352.46
  5293.7 2353.48  5361.6 2357.73  5403.5 2360.49  5425.5 2363.73  5430.5 2363.73
#Mann=5,-1,0
  4785.8    0.16       0  5007.7    0.07       0  5011.7    0.16       0
  5269.3    0.07       0  5361.6    0.16       0
Bank Sta=5007.7,5011.7
Exp/Cntr=0.3,0.1

Type RM Length L Ch R = 1,6663,109,109,109
BEGIN DESCRIPTION:
elmc810
END DESCRIPTION:
XS GIS Cut Line= 3
      1503405.39      6761547.86      1503654.09      6761560.88
      1504145.02      6761497.07
#Sta/Elev= 30
  4749.8 2361.05  4799.5 2359.52  4847.7 2355.60  4859.6 2354.34  4889.6 2353.14
  4919.6 2349.79  4939.7 2348.46  4959.7 2346.41  4969.7 2346.06  4989.7 2341.03
  4996.8 2337.59  5007.8 2336.98  5008.1 2336.48  5011.6 2336.48  5011.8 2336.98
  5030.0 2339.95  5120.8 2344.91  5141.8 2345.27  5161.1 2346.35  5191.4 2348.30
  5210.8 2350.40  5215.9 2349.70  5251.9 2353.25  5289.9 2354.65  5342.6 2355.47
  5369.1 2355.84  5374.1 2355.09  5413.2 2358.26  5448.2 2359.95  5493.9 2363.53
#Mann=4,-1,0
  4749.8    0.07       0  4847.7    0.16       0  5007.8    0.07       0
  5011.8    0.16       0
Bank Sta=5007.8,5011.8
Exp/Cntr=0.3,0.1

Type RM Length L Ch R = 1,6554,131,131,131
BEGIN DESCRIPTION:
elmc809
END DESCRIPTION:
XS GIS Cut Line= 3
      1503366.29      6761618.17      1503708.78      6761654.63
      1504060.78      6761583.19
#Sta/Elev= 30
  4659.9 2360.49  4698.8 2359.35  4795.3 2354.22  4802.2 2354.54  4829.6 2350.90
  4879.8 2347.26  4894.7 2347.11  4930.1 2342.92  4950.2 2338.34  4970.4 2336.24
  4978.4 2334.75  4978.7 2334.25  4982.2 2334.25  4982.4 2334.75  4987.2 2336.38
  4992.2 2335.63  4999.9 2337.57  5004.3 2337.57  5009.0 2338.57  5020.9 2339.46
  5031.1 2338.91  5071.9 2344.77  5120.5 2348.35  5161.0 2354.34  5166.1 2353.73
  5211.6 2357.07  5216.7 2356.47  5262.3 2358.94  5327.0 2358.79  5363.5 2359.61
#Mann=5,-1,0
  4659.9    0.07       0  4795.3    0.16       0  4978.4    0.07       0
  4982.4    0.16       0  5120.5    0.07       0
Bank Sta=4978.4,4982.4
Exp/Cntr=0.3,0.1

Type RM Length L Ch R = 1,6423,148,148,148
BEGIN DESCRIPTION:
elmc808
END DESCRIPTION:
XS GIS Cut Line= 3
      1503316.90      6761786.14      1503698.37      6761784.84
      1503981.13      6761764.08
#Sta/Elev= 30
  4612.4 2359.48  4640.5 2358.30  4690.5 2354.19  4700.5 2354.87  4710.5 2353.54
  4740.5 2352.15  4760.5 2350.12  4840.5 2348.15  4880.5 2345.25  4900.5 2344.63
  4920.5 2342.94  4940.5 2339.57  4950.5 2337.11  4960.5 2336.14  4980.5 2336.44
  4993.9 2335.33  5008.6 2332.95  5008.8 2332.45  5012.6 2332.95  5017.3 2334.58
  5030.6 2336.17  5060.7 2344.75  5089.5 2347.87  5110.8 2349.09  5120.8 2350.51
  5155.8 2351.94  5171.0 2353.81  5201.1 2355.15  5221.1 2358.29  5277.4 2361.17
#Mann=4,-1,0
  4612.4    0.16       0  5008.6    0.07       0  5012.6    0.16       0
  5089.5    0.07       0
Bank Sta=5008.6,5012.6
Exp/Cntr=0.3,0.1

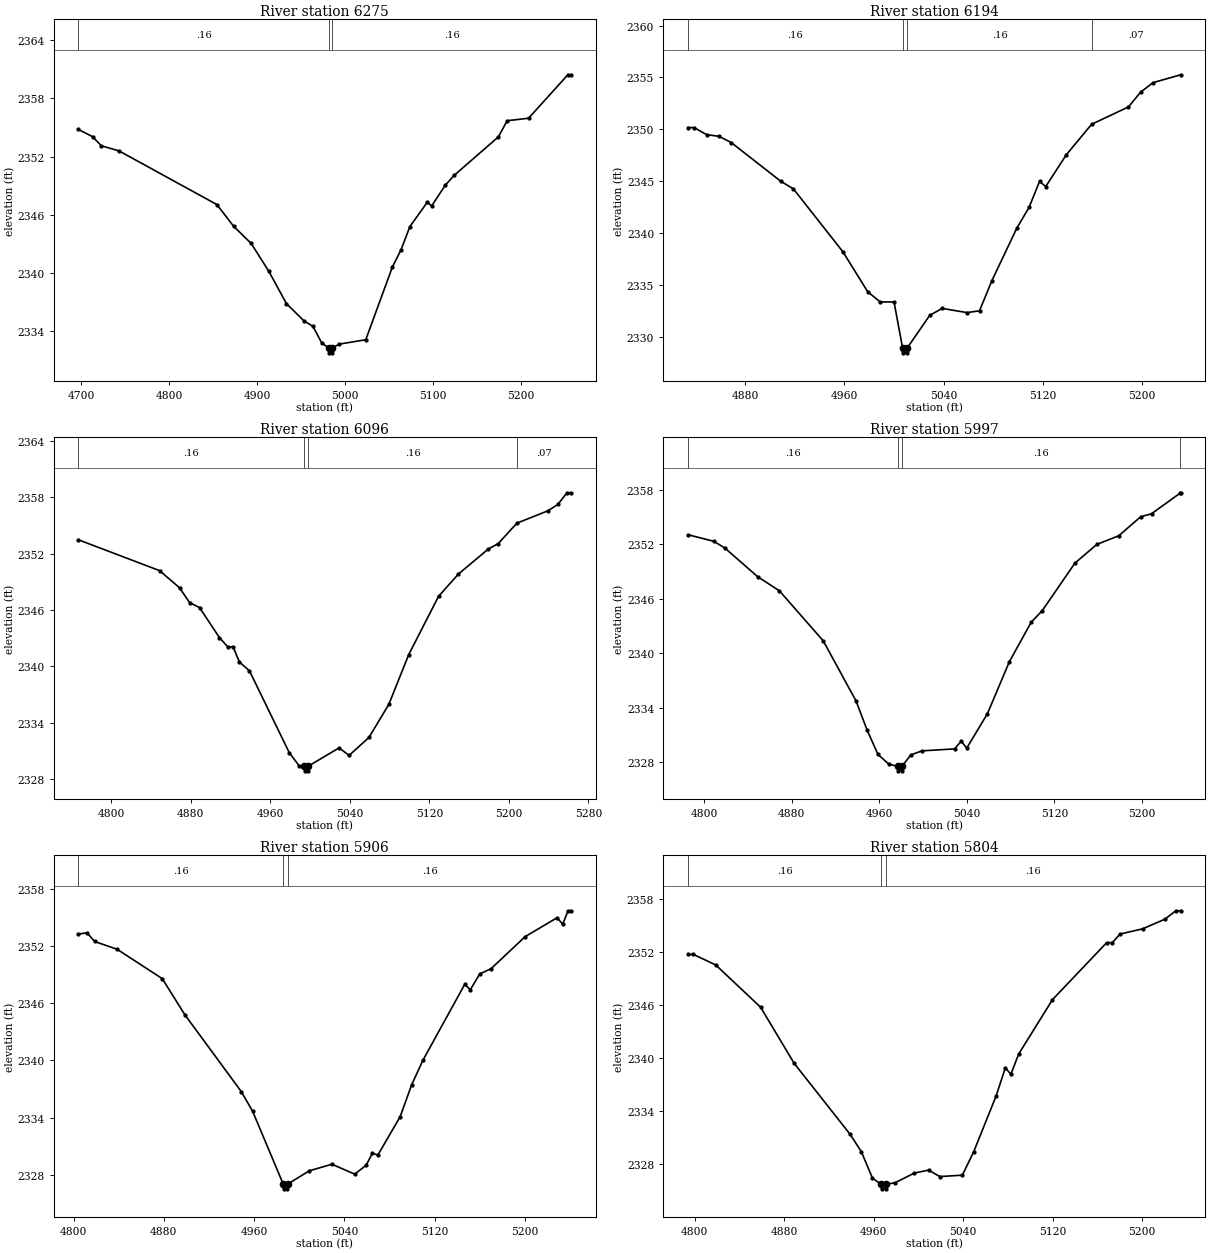
Type RM Length L Ch R = 1,6275,81,81,81
BEGIN DESCRIPTION:
elmc807
END DESCRIPTION:
XS GIS Cut Line= 3
      1503398.92      6761913.75      1503700.97      6761931.97
      1503957.50      6761908.53
#Sta/Elev= 30
  4696.6 2354.80  4712.7 2354.06  4722.7 2353.12  4742.8 2352.59  4854.1 2347.05
  4873.0 2344.82  4893.0 2343.05  4913.1 2340.17  4933.1 2336.84  4953.1 2335.05
  4963.2 2334.50  4973.2 2332.79  4981.2 2332.26  4981.5 2331.76  4985.0 2331.76
  4985.2 2332.26  4993.2 2332.66  5023.3 2333.11  5053.5 2340.60  5063.5 2342.41
  5073.5 2344.79  5093.2 2347.29  5098.2 2346.91  5113.7 2349.05  5123.7 2350.06
  5174.0 2354.03  5184.0 2355.70  5208.4 2355.96  5253.0 2360.44  5256.8 2360.44
#Mann=3,-1,0
  4696.6    0.16       0  4981.2    0.07       0  4985.2    0.16       0
Bank Sta=4981.2,4985.2
Exp/Cntr=0.3,0.1

Type RM Length L Ch R = 1,6194,98,98,98
BEGIN DESCRIPTION:
elmc378
END DESCRIPTION:
XS GIS Cut Line= 3
      1503490.02      6761999.68      1503656.22      6761998.51
      1503887.18      6761987.96
#Sta/Elev= 30
  4833.8 2350.17  4838.8 2350.17  4848.8 2349.49  4858.8 2349.33  4868.8 2348.72
  4908.8 2344.98  4918.8 2344.27  4958.8 2338.19  4978.8 2334.34  4988.8 2333.37
  5000.0 2333.36  5006.8 2328.96  5007.0 2328.46  5010.5 2328.46  5010.8 2328.96
  5028.8 2332.08  5038.8 2332.74  5058.8 2332.34  5068.9 2332.51  5078.9 2335.42
  5098.9 2340.46  5108.9 2342.49  5117.3 2344.98  5122.3 2344.49  5138.9 2347.55
  5159.3 2350.49  5189.0 2352.16  5199.0 2353.61  5209.0 2354.51  5231.2 2355.26
#Mann=4,-1,0
  4833.8    0.16       0  5006.8    0.07       0  5010.8    0.16       0
  5159.3    0.07       0
Bank Sta=5006.8,5010.8
Exp/Cntr=0.3,0.1

Type RM Length L Ch R = 1,6096,99,99,99
BEGIN DESCRIPTION:
elmc806
END DESCRIPTION:
XS GIS Cut Line= 3
      1503423.63      6762116.87      1503654.09      6762096.04
      1503918.39      6762094.73
#Sta/Elev= 30
  4767.0 2353.49  4848.7 2350.20  4868.8 2348.37  4878.8 2346.80  4888.9 2346.26
  4908.9 2343.06  4917.5 2342.05  4922.5 2342.09  4929.0 2340.46  4939.1 2339.52
  4979.2 2330.78  4989.3 2329.37  4994.3 2329.36  4994.6 2328.86  4998.1 2328.86
  4998.3 2329.36  5029.3 2331.31  5039.3 2330.50  5059.3 2332.42  5079.3 2335.95
  5099.3 2341.25  5129.3 2347.46  5149.3 2349.84  5179.3 2352.50  5189.3 2353.08
  5208.1 2355.26  5239.3 2356.58  5249.3 2357.26  5258.5 2358.50  5262.7 2358.50
#Mann=4,-1,0
  4767.0    0.16       0  4994.3    0.07       0  4998.3    0.16       0
  5208.1    0.07       0
Bank Sta=4994.3,4998.3
Exp/Cntr=0.3,0.1

Type RM Length L Ch R = 1,5997,91,91,91
BEGIN DESCRIPTION:
elmc805
END DESCRIPTION:
XS GIS Cut Line= 3
      1503431.43      6762193.69      1503651.49      6762193.69
      1503881.67      6762188.52
#Sta/Elev= 30
  4785.1 2353.07  4808.7 2352.34  4818.7 2351.61  4848.7 2348.45  4868.7 2346.88
  4908.7 2341.37  4938.7 2334.74  4948.7 2331.56  4958.7 2328.85  4968.7 2327.77
  4976.7 2327.54  4976.9 2327.04  4980.4 2327.04  4980.7 2327.54  4988.7 2328.79
  4998.7 2329.24  5028.7 2329.46  5034.8 2330.31  5039.8 2329.54  5058.7 2333.33
  5078.7 2339.05  5098.7 2343.42  5108.7 2344.68  5138.7 2349.94  5158.7 2352.00
  5178.7 2352.95  5198.7 2355.04  5208.7 2355.38  5234.8 2357.65  5235.4 2357.69
#Mann=4,-1,0
  4785.1    0.16       0  4976.7    0.07       0  4980.7    0.16       0
  5234.8    0.07       0
Bank Sta=4976.7,4980.7
Exp/Cntr=0.3,0.1

Type RM Length L Ch R = 1,5906,102,102,102
BEGIN DESCRIPTION:
elmc804
END DESCRIPTION:
XS GIS Cut Line= 3
      1503410.65      6762262.70      1503598.10      6762271.82
      1503845.52      6762241.87
#Sta/Elev= 30
  4804.2 2353.26  4811.9 2353.39  4818.6 2352.48  4838.6 2351.66  4878.6 2348.58
  4898.7 2344.78  4948.7 2336.73  4958.7 2334.67  4985.8 2327.04  4986.1 2326.54
  4989.6 2326.54  4989.8 2327.04  5008.9 2328.43  5029.0 2329.12  5049.2 2328.08
  5059.3 2329.01  5064.8 2330.25  5069.8 2330.10  5089.5 2334.11  5099.6 2337.43
  5109.6 2340.01  5146.7 2347.98  5151.7 2347.42  5160.0 2349.07  5170.1 2349.63
  5200.3 2352.99  5228.6 2354.97  5233.6 2354.29  5238.3 2355.70  5241.1 2355.70
#Mann=3,-1,0
  4804.2    0.16       0  4985.8    0.07       0  4989.8    0.16       0
Bank Sta=4985.8,4989.8
Exp/Cntr=0.3,0.1

Type RM Length L Ch R = 1,5804,105,105,105
BEGIN DESCRIPTION:
elmc803
END DESCRIPTION:
XS GIS Cut Line= 3
      1503400.18      6762379.89      1503604.62      6762372.08
      1503838.99      6762346.04
#Sta/Elev= 30
  4794.1 2351.74  4799.0 2351.74  4818.9 2350.55  4859.0 2345.76  4889.0 2339.40
  4939.0 2331.35  4949.0 2329.39  4959.0 2326.38  4967.0 2325.67  4967.3 2325.17
  4970.8 2325.17  4971.0 2325.67  4979.3 2325.87  4996.4 2326.96  5009.1 2327.29
  5019.2 2326.56  5039.3 2326.72  5049.4 2329.36  5069.5 2335.70  5077.7 2338.88
  5082.7 2338.16  5089.6 2340.44  5119.8 2346.61  5168.3 2353.08  5173.3 2353.08
  5180.2 2354.05  5200.3 2354.64  5220.4 2355.74  5230.0 2356.69  5234.5 2356.69
#Mann=3,-1,0
  4794.1    0.16       0  4967.0    0.07       0  4971.0    0.16       0
Bank Sta=4967,4971
Exp/Cntr=0.3,0.1

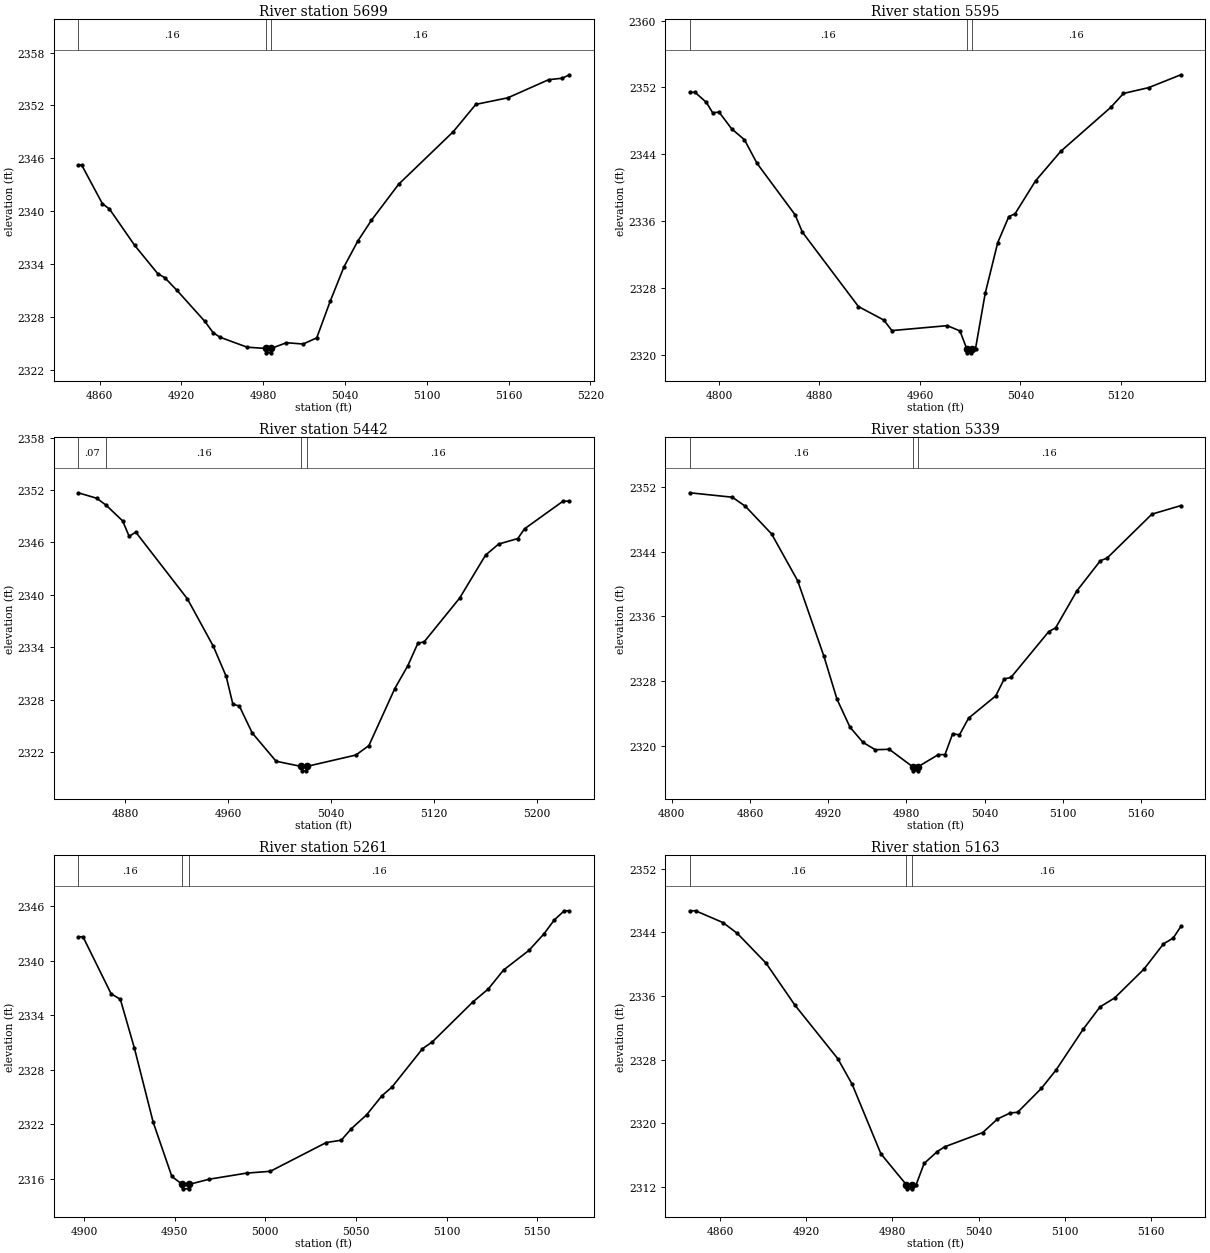
Type RM Length L Ch R = 1,5699,104,104,104
BEGIN DESCRIPTION:
elmc377
END DESCRIPTION:
XS GIS Cut Line= 3
      1503455.04      6762438.01      1503605.67      6762477.03
      1503810.18      6762471.04
#Sta/Elev= 30
  4844.4 2345.23  4846.9 2345.23  4862.1 2340.83  4867.2 2340.25  4885.7 2336.12
  4902.7 2332.89  4907.8 2332.44  4916.7 2331.01  4937.3 2327.46  4943.3 2326.19
  4948.4 2325.67  4968.3 2324.54  4981.9 2324.40  4982.1 2323.90  4985.6 2323.90
  4985.9 2324.40  4997.1 2325.05  5009.3 2324.90  5019.3 2325.60  5029.3 2329.81
  5039.3 2333.67  5049.4 2336.59  5059.4 2338.95  5079.4 2343.05  5119.4 2349.01
  5136.0 2352.12  5159.4 2352.86  5189.4 2354.92  5199.4 2355.09  5204.6 2355.48
#Mann=3,-1,0
  4844.4    0.16       0  4981.9    0.07       0  4985.9    0.16       0
Bank Sta=4981.9,4985.9
Exp/Cntr=0.3,0.1

Type RM Length L Ch R = 1,5595,153,153,153
BEGIN DESCRIPTION:
elmc802
END DESCRIPTION:
XS GIS Cut Line= 3
      1503381.96      6762550.46      1503604.62      6762581.71
      1503770.65      6762588.20
#Sta/Elev= 30
  4776.8 2351.43  4780.9 2351.43  4790.0 2350.22  4795.0 2348.98  4800.1 2349.06
  4810.2 2347.05  4820.3 2345.76  4830.4 2342.92  4860.7 2336.77  4866.4 2334.72
  4911.1 2325.81  4931.3 2324.20  4937.7 2322.94  4981.8 2323.53  4991.9 2322.90
  4997.3 2320.78  4997.6 2320.28  5001.1 2320.28  5001.3 2320.78  5004.3 2320.78
  5012.0 2327.38  5022.0 2333.46  5030.8 2336.56  5035.8 2336.91  5052.1 2340.84
  5072.1 2344.36  5112.1 2349.64  5122.1 2351.29  5142.1 2351.98  5167.8 2353.52
#Mann=3,-1,0
  4776.8    0.16       0  4997.3    0.07       0  5001.3    0.16       0
Bank Sta=4997.3,5001.3
Exp/Cntr=0.3,0.1

Type RM Length L Ch R = 1,5442,103,103,103
BEGIN DESCRIPTION:
elmc801
END DESCRIPTION:
XS GIS Cut Line= 3
      1503350.75      6762678.07      1503506.96      6762697.60
      1503729.63      6762667.65
#Sta/Elev= 30
  4843.3 2351.69  4857.7 2351.06  4865.1 2350.25  4877.8 2348.47  4882.9 2346.70
  4888.0 2347.19  4928.2 2339.54  4948.4 2334.10  4958.4 2330.65  4963.6 2327.46
  4968.6 2327.27  4978.6 2324.19  4997.2 2320.94  5016.9 2320.34  5017.2 2319.84
  5020.7 2319.84  5020.9 2320.34  5059.3 2321.65  5069.4 2322.73  5089.6 2329.27
  5099.7 2331.88  5107.5 2334.44  5112.5 2334.63  5140.0 2339.62  5160.2 2344.55
  5170.3 2345.81  5185.3 2346.45  5190.5 2347.56  5220.5 2350.73  5225.4 2350.73
#Mann=4,-1,0
  4843.3    0.07       0  4865.1    0.16       0  5016.9    0.07       0
  5020.9    0.16       0
Bank Sta=5016.9,5020.9
Exp/Cntr=0.3,0.1

Type RM Length L Ch R = 1,5339,78,78,78
BEGIN DESCRIPTION:
elmc800
END DESCRIPTION:
XS GIS Cut Line= 3
      1503362.46      6762773.12      1503555.14      6762786.14
      1503731.75      6762737.15
#Sta/Elev= 30
  4813.9 2351.33  4846.5 2350.78  4856.5 2349.66  4876.6 2346.23  4896.6 2340.42
  4916.7 2331.07  4926.7 2325.76  4936.7 2322.27  4946.7 2320.38  4956.1 2319.48
  4966.8 2319.53  4984.8 2317.36  4985.1 2316.86  4988.6 2316.86  4988.8 2317.36
  5004.4 2318.87  5009.5 2318.87  5015.4 2321.46  5020.6 2321.32  5027.6 2323.39
  5048.4 2326.15  5054.9 2328.25  5060.1 2328.44  5089.1 2334.13  5094.3 2334.58
  5110.6 2339.17  5128.6 2342.91  5133.8 2343.24  5168.1 2348.68  5190.3 2349.74
#Mann=3,-1,0
  4813.9    0.16       0  4984.8    0.07       0  4988.8    0.16       0
Bank Sta=4984.8,4988.8
Exp/Cntr=0.3,0.1

Type RM Length L Ch R = 1,5261,98,98,98
BEGIN DESCRIPTION:
elmc376
END DESCRIPTION:
XS GIS Cut Line= 3
      1503454.97      6762888.01      1503554.99      6762863.00
      1503704.99      6762788.01
#Sta/Elev= 30
  4896.9 2342.65  4899.5 2342.65  4915.0 2336.38  4920.1 2335.77  4927.9 2330.36
  4938.2 2322.25  4948.5 2316.28  4954.2 2315.42  4954.4 2314.92  4957.9 2314.92
  4958.2 2315.42  4969.1 2315.98  4989.7 2316.65  5002.8 2316.85  5033.6 2320.01
  5041.9 2320.27  5047.5 2321.54  5055.9 2323.06  5064.3 2325.15  5069.9 2326.12
  5086.7 2330.33  5092.2 2331.10  5114.6 2335.50  5123.0 2336.91  5131.4 2338.99
  5145.4 2341.15  5153.7 2342.97  5159.3 2344.48  5164.9 2345.51  5167.7 2345.51
#Mann=3,-1,0
  4896.9    0.16       0  4954.2    0.07       0  4958.2    0.16       0
Bank Sta=4954.2,4958.2
Exp/Cntr=0.3,0.1

Type RM Length L Ch R = 1,5163,89,89,89
BEGIN DESCRIPTION:
elmc799
END DESCRIPTION:
XS GIS Cut Line= 3
      1503411.95      6762961.92      1503569.46      6762956.71
      1503750.23      6762920.30
#Sta/Elev= 30
  4838.9 2346.71  4842.9 2346.71  4862.0 2345.23  4872.0 2343.87  4892.0 2340.13
  4912.0 2334.88  4942.0 2328.12  4952.0 2324.90  4972.0 2316.17  4989.8 2312.27
  4990.0 2311.77  4993.5 2311.77  4993.8 2312.27  4996.5 2312.27  5002.1 2314.96
  5011.3 2316.46  5016.4 2317.05  5042.9 2318.84  5053.2 2320.55  5062.1 2321.31
  5067.2 2321.39  5083.8 2324.40  5094.0 2326.71  5112.9 2331.83  5124.6 2334.63
  5134.8 2335.76  5155.2 2339.38  5168.8 2342.55  5175.6 2343.29  5180.9 2344.74
#Mann=3,-1,0
  4838.9    0.16       0  4989.8    0.07       0  4993.8    0.16       0
Bank Sta=4989.8,4993.8
Exp/Cntr=0.3,0.1

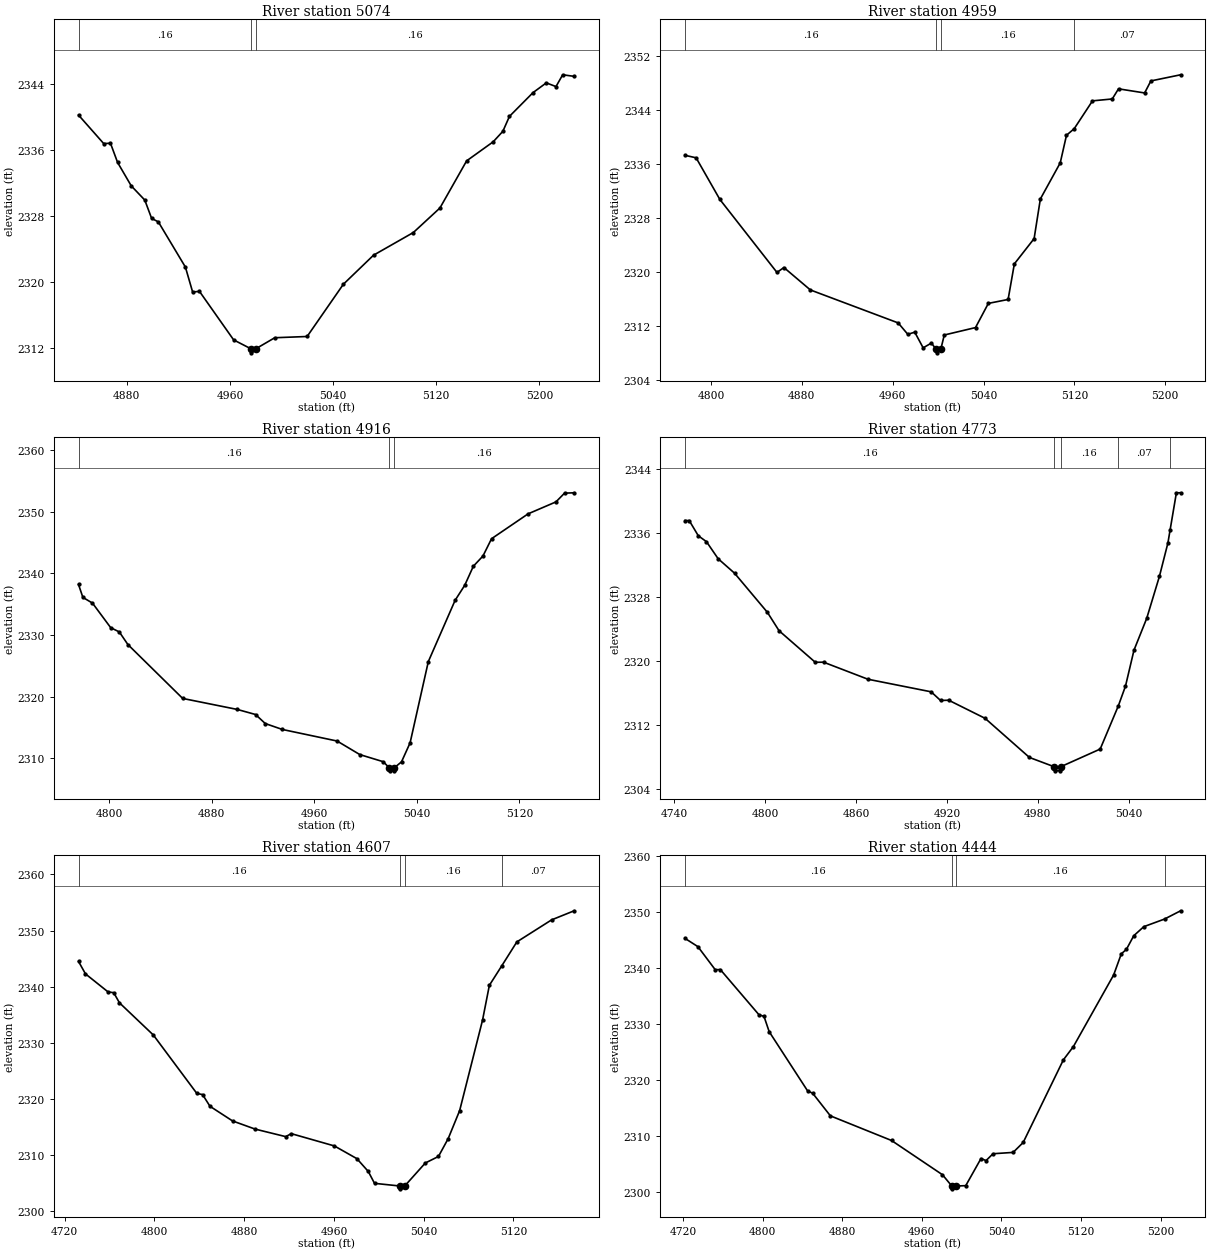
Type RM Length L Ch R = 1,5074,115,115,115
BEGIN DESCRIPTION:
elmc798
END DESCRIPTION:
XS GIS Cut Line= 3
      1503456.18      6762985.36      1503607.22      6763034.84
      1503825.95      6762980.15
#Sta/Elev= 30
  4842.6 2340.23  4862.1 2336.78  4867.4 2336.81  4872.9 2334.49  4883.5 2331.65
  4894.0 2329.93  4899.3 2327.71  4904.5 2327.29  4925.5 2321.81  4931.1 2318.79
  4936.4 2318.87  4962.9 2312.99  4976.2 2311.92  4976.4 2311.42  4980.2 2311.92
  4994.8 2313.25  5019.9 2313.40  5048.0 2319.73  5071.4 2323.25  5102.3 2326.00
  5122.9 2328.97  5143.6 2334.68  5164.2 2336.99  5171.7 2338.26  5176.8 2340.07
  5195.1 2342.95  5205.4 2344.13  5212.9 2343.68  5218.1 2345.11  5227.0 2344.92
#Mann=3,-1,0
  4842.6    0.16       0  4976.2    0.07       0  4980.2    0.16       0
Bank Sta=4976.2,4980.2
Exp/Cntr=0.3,0.1

Type RM Length L Ch R = 1,4959,43,43,43
BEGIN DESCRIPTION:
elmc797
END DESCRIPTION:
XS GIS Cut Line= 3
      1503465.27      6763004.87      1503650.19      6763139.00
      1503838.96      6763226.23
#Sta/Elev= 30
  4777.1 2337.24  4786.9 2336.87  4807.8 2330.71  4858.1 2319.90  4864.2 2320.63
  4887.5 2317.31  4964.8 2312.43  4973.3 2310.74  4979.4 2311.06  4986.8 2308.74
  4994.1 2309.45  4998.3 2308.50  4998.6 2308.00  5002.3 2308.50  5005.4 2310.64
  5032.9 2311.74  5044.2 2315.32  5061.6 2315.90  5067.1 2321.17  5084.5 2324.91
  5090.0 2330.78  5107.5 2336.12  5113.0 2340.21  5119.8 2341.18  5135.9 2345.30
  5153.3 2345.58  5158.8 2347.08  5181.8 2346.47  5187.3 2348.25  5213.5 2349.16
#Mann=4,-1,0
  4777.1    0.16       0  4998.3    0.07       0  5002.3    0.16       0
  5119.8    0.07       0
Bank Sta=4998.3,5002.3
Exp/Cntr=0.3,0.1

Type RM Length L Ch R = 1,4916,143,143,143
BEGIN DESCRIPTION:
elmc796
END DESCRIPTION:
XS GIS Cut Line= 3
      1503456.21      6763021.84      1503620.24      6763167.65
      1503745.22      6763278.31
#Sta/Elev= 30
  4776.3 2338.21  4779.7 2336.11  4787.2 2335.18  4801.4 2331.19  4808.1 2330.50
  4814.8 2328.45  4857.5 2319.70  4900.1 2317.91  4914.3 2317.09  4921.9 2315.62
  4935.2 2314.66  4977.9 2312.78  4995.6 2310.58  5013.9 2309.42  5018.5 2308.44
  5018.8 2307.94  5022.3 2307.94  5022.5 2308.44  5028.1 2309.40  5034.8 2312.49
  5049.0 2325.68  5069.9 2335.64  5077.4 2338.08  5084.1 2341.17  5091.6 2342.83
  5098.3 2345.64  5126.8 2349.68  5148.5 2351.62  5155.2 2353.04  5162.7 2353.10
#Mann=3,-1,0
  4776.3    0.16       0  5018.5    0.07       0  5022.5    0.16       0
Bank Sta=5018.5,5022.5
Exp/Cntr=0.3,0.1

Type RM Length L Ch R = 1,4773,166,166,166
BEGIN DESCRIPTION:
elmc375
END DESCRIPTION:
XS GIS Cut Line= 3
      1503425.47      6763037.72      1503521.77      6763271.57
      1503555.01      6763338.02
#Sta/Elev= 30
  4747.1 2337.51  4749.9 2337.51  4755.9 2335.61  4761.3 2334.87  4769.0 2332.74
  4779.8 2330.94  4801.5 2326.05  4809.2 2323.75  4833.1 2319.81  4838.6 2319.82
  4867.9 2317.69  4909.6 2316.12  4915.8 2315.04  4921.2 2315.07  4945.2 2312.81
  4974.5 2307.92  4991.0 2306.75  4991.3 2306.25  4994.8 2306.25  4995.0 2306.75
  5021.2 2308.97  5033.1 2314.33  5037.9 2316.83  5043.5 2321.32  5051.9 2325.29
  5060.3 2330.54  5065.9 2334.71  5067.3 2336.28  5071.5 2340.98  5074.3 2340.98
#Mann=5,-1,0
  4747.1    0.16       0  4991.0    0.07       0  4995.0    0.16       0
  5033.1    0.07       0  5067.3    0.16       0
Bank Sta=4991,4995
Exp/Cntr=0.3,0.1

Type RM Length L Ch R = 1,4607,163,163,163
BEGIN DESCRIPTION:
elmc795
END DESCRIPTION:
XS GIS Cut Line= 3
      1503325.97      6763021.82      1503361.13      6763292.65
      1503394.98      6763458.02
#Sta/Elev= 30
  4732.3 2344.49  4738.5 2342.27  4758.6 2339.06  4763.7 2338.91  4768.8 2337.11
  4799.0 2331.37  4837.8 2320.95  4842.9 2320.75  4849.5 2318.66  4869.6 2316.05
  4889.8 2314.59  4917.0 2313.25  4922.0 2313.78  4960.4 2311.59  4980.5 2309.32
  4990.6 2307.05  4996.2 2304.92  5019.1 2304.44  5019.3 2303.94  5023.1 2304.44
  5041.5 2308.55  5053.2 2309.71  5061.9 2312.90  5072.1 2317.89  5092.5 2334.01
  5098.6 2340.23  5109.8 2343.75  5123.1 2347.97  5154.1 2351.90  5174.2 2353.52
#Mann=4,-1,0
  4732.3    0.16       0  5019.1    0.07       0  5023.1    0.16       0
  5109.8    0.07       0
Bank Sta=5019.1,5023.1
Exp/Cntr=0.3,0.1

Type RM Length L Ch R = 1,4444,105,105,105
BEGIN DESCRIPTION:
elmc794
END DESCRIPTION:
XS GIS Cut Line= 3
      1503256.96      6763015.32      1503197.06      6763288.74
      1503228.09      6763504.62
#Sta/Elev= 30
  4722.0 2345.25  4735.0 2343.77  4752.4 2339.65  4757.5 2339.68  4796.3 2331.61
  4801.4 2331.31  4806.6 2328.58  4845.2 2318.00  4850.3 2317.58  4868.1 2313.54
  4929.5 2309.14  4980.7 2303.02  4990.1 2301.00  4990.4 2300.50  4994.1 2301.00
  5004.1 2301.07  5019.4 2305.91  5024.5 2305.55  5031.5 2306.77  5051.7 2307.01
  5061.8 2308.78  5102.2 2323.55  5112.3 2325.93  5152.7 2338.71  5160.4 2342.49
  5165.5 2343.28  5172.9 2345.72  5183.0 2347.34  5203.8 2348.70  5220.0 2350.18
#Mann=4,-1,0
  4722.0    0.16       0  4990.1    0.07       0  4994.1    0.16       0
  5203.8    0.07       0
Bank Sta=4990.1,4994.1
Exp/Cntr=0.3,0.1