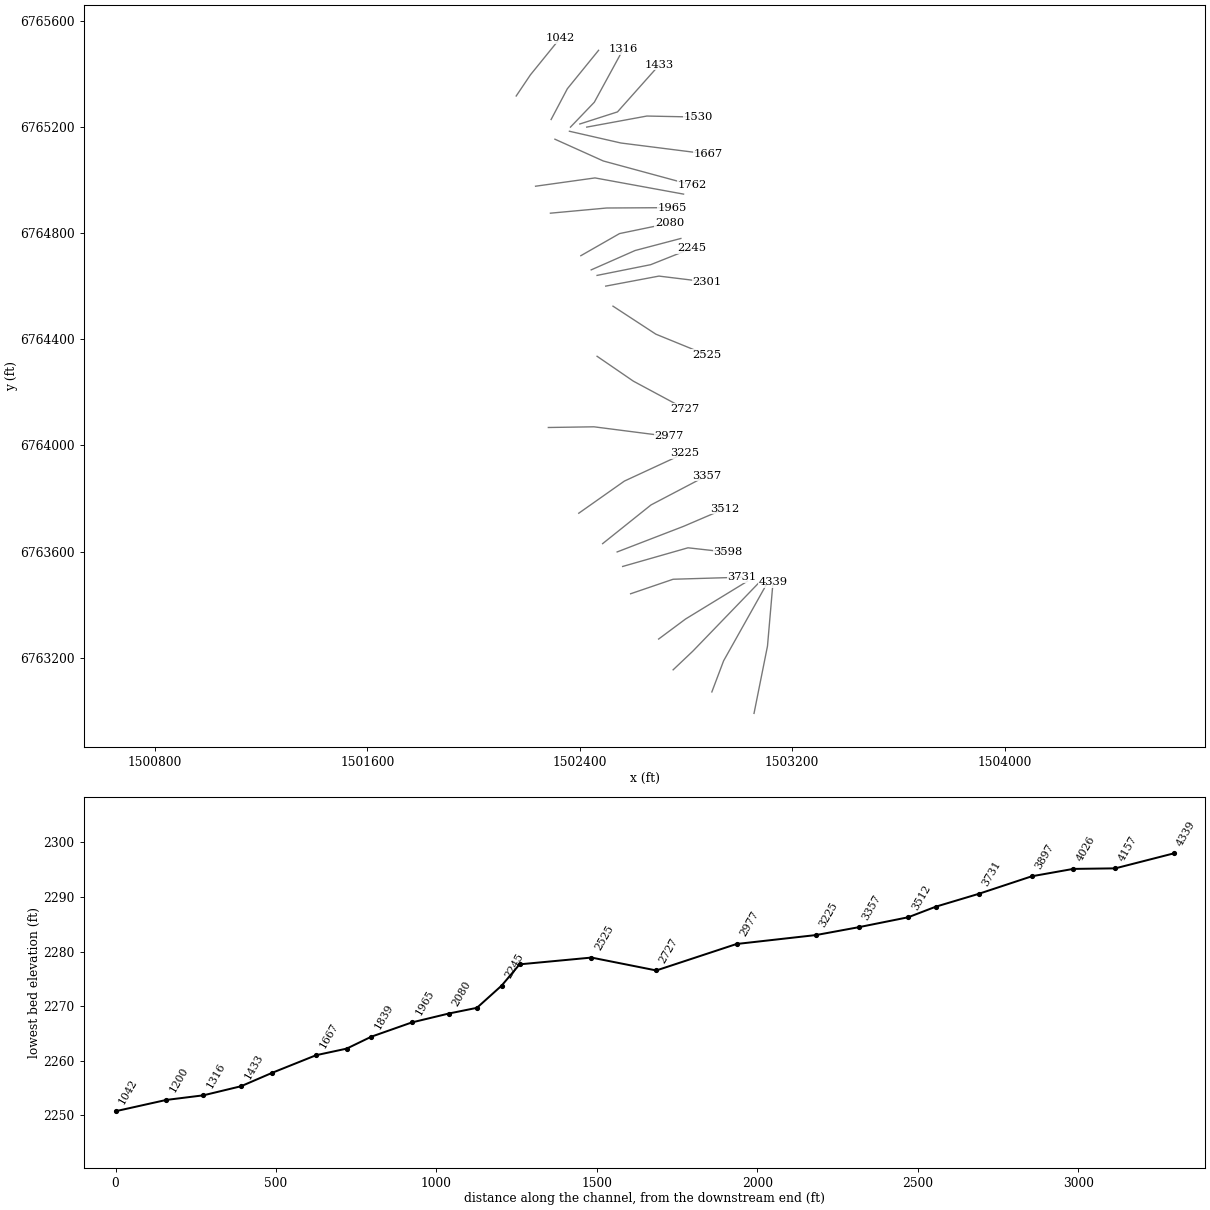
HEC-RAS study Elm 36.prj: Elm 36 Base Level Engineering

--- Elm 36.g01 (geometry) --- (continued)

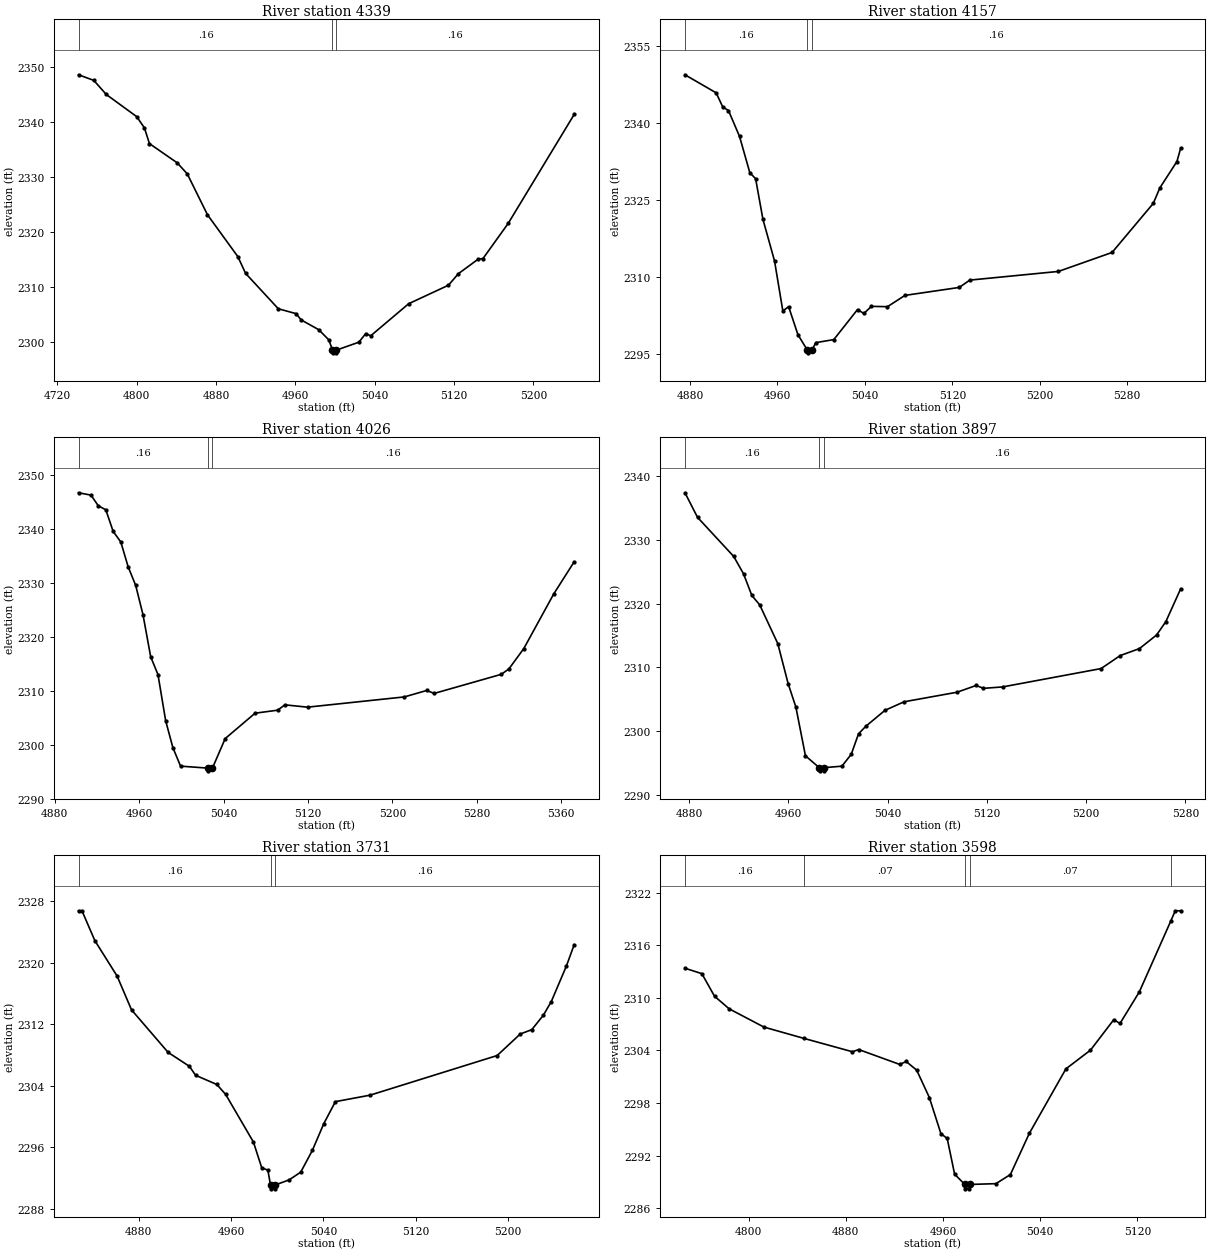
Type RM Length L Ch R = 1,4339,182,182,182
BEGIN DESCRIPTION:
elmc374
END DESCRIPTION:
XS GIS Cut Line= 3
      1503056.43      6762990.54      1503107.18      6763244.12
      1503127.95      6763484.22
#Sta/Elev= 30
  4741.4 2348.64  4756.8 2347.62  4769.4 2345.05  4800.0 2341.02  4807.8 2338.98
  4812.9 2336.10  4840.8 2332.61  4851.0 2330.59  4871.4 2323.13  4902.0 2315.51
  4909.8 2312.46  4942.8 2306.01  4960.7 2305.12  4965.8 2303.98  4983.6 2302.19
  4993.8 2300.32  4997.4 2298.48  4997.7 2297.98  5001.2 2297.98  5001.4 2298.48
  5024.0 2299.92  5030.9 2301.49  5035.9 2301.08  5074.2 2306.93  5114.3 2310.30
  5124.3 2312.40  5144.1 2315.03  5149.1 2315.16  5174.5 2321.56  5241.0 2341.41
#Mann=3,-1,0
  4741.4    0.16       0  4997.4    0.07       0  5001.4    0.16       0
Bank Sta=4997.4,5001.4
Exp/Cntr=0.3,0.1

Type RM Length L Ch R = 1,4157,131,131,131
BEGIN DESCRIPTION:
elmc793
END DESCRIPTION:
XS GIS Cut Line= 3
      1502897.60      6763071.34      1502941.85      6763188.48
      1503102.39      6763474.60
#Sta/Elev= 30
  4875.5 2349.45  4904.0 2345.93  4910.0 2343.20  4915.3 2342.47  4925.4 2337.43
  4934.8 2330.36  4940.1 2329.19  4946.8 2321.26  4957.4 2313.16  4965.0 2303.42
  4970.3 2304.23  4978.8 2298.78  4987.5 2295.74  4987.8 2295.24  4991.5 2295.74
  4995.2 2297.23  5011.6 2297.82  5033.3 2303.68  5039.1 2302.91  5046.0 2304.30
  5060.7 2304.24  5076.7 2306.44  5126.3 2307.99  5136.0 2309.42  5217.0 2311.11
  5266.1 2314.81  5303.8 2324.38  5309.8 2327.40  5325.4 2332.54  5328.8 2335.10
#Mann=3,-1,0
  4875.5    0.16       0  4987.5    0.07       0  4991.5    0.16       0
Bank Sta=4987.5,4991.5
Exp/Cntr=0.3,0.1

Type RM Length L Ch R = 1,4026,129,129,129
BEGIN DESCRIPTION:
elmc792
END DESCRIPTION:
XS GIS Cut Line= 3
      1502751.75      6763154.63      1502825.97      6763224.94
      1503081.23      6763489.27
#Sta/Elev= 30
  4902.6 2346.67  4914.4 2346.24  4921.3 2344.27  4928.5 2343.51  4935.4 2339.53
  4942.7 2337.54  4949.6 2332.97  4956.8 2329.50  4963.7 2324.08  4971.0 2316.27
  4977.9 2312.98  4985.2 2304.41  4992.0 2299.46  4999.3 2296.01  5025.5 2295.64
  5025.7 2295.14  5029.5 2295.64  5041.6 2301.12  5069.9 2305.82  5091.3 2306.38
  5098.2 2307.37  5119.6 2306.94  5211.4 2308.84  5232.5 2310.03  5239.7 2309.49
  5303.3 2313.03  5310.5 2314.04  5324.6 2317.81  5352.9 2327.91  5372.3 2333.88
#Mann=3,-1,0
  4902.6    0.16       0  5025.5    0.07       0  5029.5    0.16       0
Bank Sta=5025.5,5029.5
Exp/Cntr=0.3,0.1

Type RM Length L Ch R = 1,3897,166,166,166
BEGIN DESCRIPTION:
elmc791
END DESCRIPTION:
XS GIS Cut Line= 3
      1502697.09      6763270.53      1502798.63      6763346.04
      1503031.54      6763488.37
#Sta/Elev= 30
  4876.7 2337.40  4886.8 2333.55  4916.0 2327.41  4923.9 2324.69  4930.6 2321.29
  4936.9 2319.83  4951.5 2313.75  4959.9 2307.43  4966.1 2303.78  4973.8 2296.15
  4984.9 2294.29  4985.2 2293.79  4988.7 2293.79  4988.9 2294.29  5003.2 2294.52
  5010.7 2296.38  5016.6 2299.60  5022.4 2300.77  5037.9 2303.28  5053.3 2304.62
  5096.0 2306.12  5111.4 2307.18  5117.3 2306.73  5132.7 2306.95  5212.1 2309.83
  5227.5 2311.87  5243.0 2312.96  5256.8 2315.09  5264.3 2317.20  5276.2 2322.33
#Mann=3,-1,0
  4876.7    0.16       0  4984.9    0.07       0  4988.9    0.16       0
Bank Sta=4984.9,4988.9
Exp/Cntr=0.3,0.1

Type RM Length L Ch R = 1,3731,133,133,133
BEGIN DESCRIPTION:
elmc790
END DESCRIPTION:
XS GIS Cut Line= 3
      1502591.59      6763441.09      1502751.75      6763495.78
      1503011.70      6763503.53
#Sta/Elev= 30
  4827.9 2326.75  4830.9 2326.75  4842.1 2322.85  4861.3 2318.26  4873.8 2313.86
  4905.5 2308.32  4924.0 2306.50  4929.3 2305.34  4947.7 2304.14  4955.3 2302.86
  4979.4 2296.65  4986.6 2293.30  4991.9 2292.99  4994.2 2291.06  4994.5 2290.56
  4998.0 2290.56  4998.2 2291.06  5010.4 2291.73  5020.4 2292.74  5030.4 2295.55
  5040.4 2299.06  5050.4 2301.91  5080.4 2302.75  5190.5 2307.91  5210.5 2310.71
  5220.5 2311.28  5230.5 2313.15  5237.4 2314.94  5250.5 2319.57  5257.2 2322.33
#Mann=3,-1,0
  4827.9    0.16       0  4994.2    0.07       0  4998.2    0.16       0
Bank Sta=4994.2,4998.2
Exp/Cntr=0.3,0.1

Type RM Length L Ch R = 1,3598,86,86,86
BEGIN DESCRIPTION:
elmc789
END DESCRIPTION:
XS GIS Cut Line= 3
      1502561.66      6763543.96      1502807.74      6763614.26
      1502958.77      6763597.34
#Sta/Elev= 30
  4747.6 2313.37  4761.5 2312.75  4771.9 2310.18  4784.0 2308.74  4812.6 2306.66
  4845.8 2305.36  4885.4 2303.85  4890.6 2304.10  4924.4 2302.40  4929.6 2302.74
  4938.3 2301.75  4948.7 2298.63  4958.2 2294.52  4963.4 2293.96  4969.5 2289.89
  4977.9 2288.72  4978.1 2288.22  4981.6 2288.22  4981.9 2288.72  5003.5 2288.81
  5015.4 2289.85  5031.0 2294.55  5061.1 2301.90  5081.3 2304.03  5100.5 2307.51
  5105.6 2307.07  5121.5 2310.67  5147.3 2318.72  5151.1 2319.92  5155.5 2319.92
#Mann=5,-1,0
  4747.6    0.16       0  4845.8    0.07       0  4977.9    0.07       0
  4981.9    0.07       0  5147.3    0.16       0
Bank Sta=4977.9,4981.9
Exp/Cntr=0.3,0.1

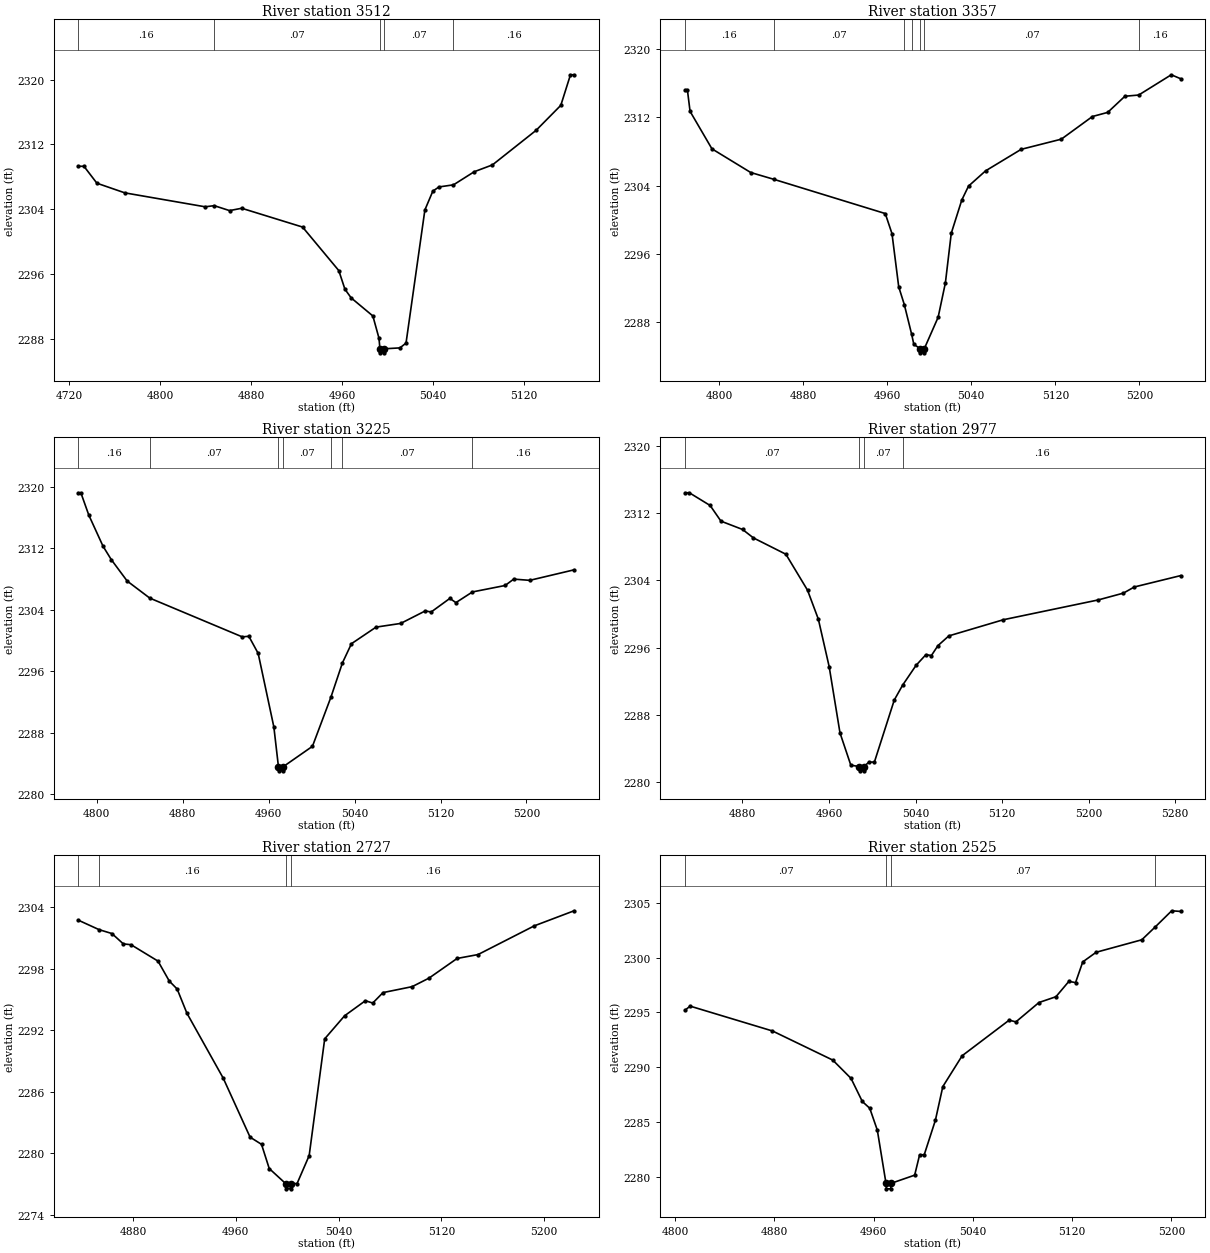
Type RM Length L Ch R = 1,3512,155,155,155
BEGIN DESCRIPTION:
elmc788
END DESCRIPTION:
XS GIS Cut Line= 3
      1502540.84      6763598.65      1502790.81      6763694.99
      1502945.79      6763761.41
#Sta/Elev= 30
  4727.9 2309.30  4732.8 2309.30  4744.2 2307.21  4768.8 2306.02  4839.5 2304.30
  4847.5 2304.44  4861.0 2303.83  4871.7 2304.12  4925.3 2301.80  4957.2 2296.43
  4962.6 2294.13  4968.1 2293.06  4987.2 2290.83  4992.6 2288.08  4993.4 2286.78
  4993.6 2286.28  4997.1 2286.28  4997.4 2286.78  5011.0 2286.89  5016.4 2287.48
  5033.0 2303.91  5040.0 2306.23  5045.4 2306.75  5058.2 2307.01  5076.5 2308.63
  5092.5 2309.47  5130.9 2313.73  5152.7 2316.82  5161.2 2320.59  5164.4 2320.59
#Mann=5,-1,0
  4727.9    0.16       0  4847.5    0.07       0  4993.4    0.07       0
  4997.4    0.07       0  5058.2    0.16       0
Bank Sta=4993.4,4997.4
Exp/Cntr=0.3,0.1

Type RM Length L Ch R = 1,3357,132,132,132
BEGIN DESCRIPTION:
elmc787
END DESCRIPTION:
XS GIS Cut Line= 3
      1502486.15      6763629.91      1502668.42      6763775.72
      1502879.33      6763886.39
#Sta/Elev= 30
  4767.6 2315.16  4770.0 2315.16  4772.5 2312.69  4793.3 2308.31  4830.2 2305.54
  4852.3 2304.74  4958.2 2300.74  4964.6 2298.39  4971.0 2292.17  4976.3 2290.10
  4983.3 2286.62  4985.4 2285.43  4991.4 2284.95  4991.7 2284.45  4995.2 2284.45
  4995.4 2284.95  5008.5 2288.61  5015.4 2292.63  5021.0 2298.44  5031.0 2302.32
  5037.4 2303.95  5053.6 2305.73  5087.5 2308.25  5125.7 2309.44  5155.3 2312.09
  5169.8 2312.57  5186.2 2314.46  5199.3 2314.60  5230.3 2316.97  5239.2 2316.51
#Mann=7,-1,0
  4767.6    0.16       0  4852.3    0.07       0  4976.3    0.16       0
  4983.3    0.07       0  4991.4    0.07       0  4995.4    0.07       0
  5199.3    0.16       0
Bank Sta=4991.4,4995.4
Exp/Cntr=0.3,0.1

Type RM Length L Ch R = 1,3225,248,248,248
BEGIN DESCRIPTION:
elmc786
END DESCRIPTION:
XS GIS Cut Line= 3
      1502396.28      6763744.47      1502568.16      6763865.57
      1502795.99      6763971.02
#Sta/Elev= 30
  4783.0 2319.22  4785.3 2319.22  4792.7 2316.31  4805.9 2312.27  4813.6 2310.52
  4828.4 2307.73  4849.4 2305.51  4935.5 2300.46  4941.6 2300.54  4950.3 2298.31
  4964.9 2288.73  4969.2 2283.52  4969.5 2283.02  4973.0 2283.02  4973.2 2283.52
  5000.8 2286.21  5018.0 2292.61  5028.7 2297.07  5037.1 2299.57  5060.0 2301.73
  5082.9 2302.21  5105.8 2303.84  5111.3 2303.70  5128.7 2305.47  5134.3 2304.92
  5149.7 2306.31  5180.1 2307.15  5188.1 2307.98  5203.0 2307.82  5244.3 2309.19
#Mann=7,-1,0
  4783.0    0.16       0  4849.4    0.07       0  4969.2    0.07       0
  4973.2    0.07       0  5018.0    0.16       0  5028.7    0.07       0
  5149.7    0.16       0
Bank Sta=4969.2,4973.2
Exp/Cntr=0.3,0.1

Type RM Length L Ch R = 1,2977,250,250,250
BEGIN DESCRIPTION:
elmc785
END DESCRIPTION:
XS GIS Cut Line= 3
      1502281.71      6764067.39      1502453.57      6764069.99
      1502737.46      6764033.53
#Sta/Elev= 30
  4826.9 2314.41  4831.0 2314.41  4850.2 2312.90  4860.2 2311.04  4880.2 2310.05
  4890.2 2309.05  4920.2 2307.11  4940.2 2302.84  4950.2 2299.40  4960.2 2293.76
  4970.2 2285.89  4980.2 2282.06  4988.2 2281.88  4988.5 2281.38  4992.0 2281.38
  4992.2 2281.88  4997.0 2282.42  5002.0 2282.42  5020.4 2289.80  5028.1 2291.56
  5040.5 2293.91  5049.6 2295.18  5054.7 2295.08  5060.7 2296.25  5070.8 2297.41
  5121.2 2299.33  5208.8 2301.68  5232.1 2302.49  5242.2 2303.22  5285.0 2304.57
#Mann=4,-1,0
  4826.9    0.07       0  4988.2    0.07       0  4992.2    0.07       0
  5028.1    0.16       0
Bank Sta=4988.2,4992.2
Exp/Cntr=0.3,0.1

Type RM Length L Ch R = 1,2727,202,202,202
BEGIN DESCRIPTION:
elmc784
END DESCRIPTION:
XS GIS Cut Line= 3
      1502465.31      6764335.60      1502602.01      6764241.87
      1502796.06      6764137.68
#Sta/Elev= 30
  4837.4 2302.73  4853.5 2301.81  4863.5 2301.43  4872.4 2300.42  4878.4 2300.34
  4899.4 2298.74  4908.2 2296.79  4914.3 2296.02  4921.9 2293.66  4950.2 2287.32
  4971.1 2281.57  4980.0 2280.87  4986.0 2278.51  4998.9 2277.03  4999.2 2276.53
  5002.7 2276.53  5002.9 2277.03  5007.7 2277.05  5017.1 2279.77  5029.2 2291.16
  5044.7 2293.41  5060.9 2294.88  5066.6 2294.65  5074.6 2295.67  5097.3 2296.25
  5110.4 2297.08  5132.3 2299.00  5148.6 2299.38  5192.4 2302.18  5223.4 2303.65
#Mann=4,-1,0
  4837.4    0.07       0  4853.5    0.16       0  4998.9    0.07       0
  5002.9    0.16       0
Bank Sta=4998.9,5002.9
Exp/Cntr=0.3,0.1

Type RM Length L Ch R = 1,2525,224,224,224
BEGIN DESCRIPTION:
elmc783
END DESCRIPTION:
XS GIS Cut Line= 3
      1502525.18      6764524.42      1502686.65      6764418.95
      1502878.06      6764340.83
#Sta/Elev= 30
  4807.8 2295.20  4812.0 2295.58  4878.4 2293.31  4927.0 2290.65  4941.7 2288.98
  4950.8 2286.87  4956.8 2286.25  4962.9 2284.25  4969.9 2279.39  4970.2 2278.89
  4973.7 2278.89  4973.9 2279.39  4993.0 2280.14  4997.0 2282.00  5000.7 2282.00
  5009.7 2285.15  5015.7 2288.23  5031.3 2291.05  5069.2 2294.30  5074.6 2294.14
  5093.2 2295.91  5106.9 2296.44  5117.3 2297.84  5122.7 2297.73  5128.5 2299.62
  5139.3 2300.50  5176.1 2301.64  5186.8 2302.80  5200.2 2304.29  5207.4 2304.23
#Mann=4,-1,0
  4807.8    0.07       0  4969.9    0.07       0  4973.9    0.07       0
  5186.8    0.16       0
Bank Sta=4969.9,4973.9
Exp/Cntr=0.3,0.1

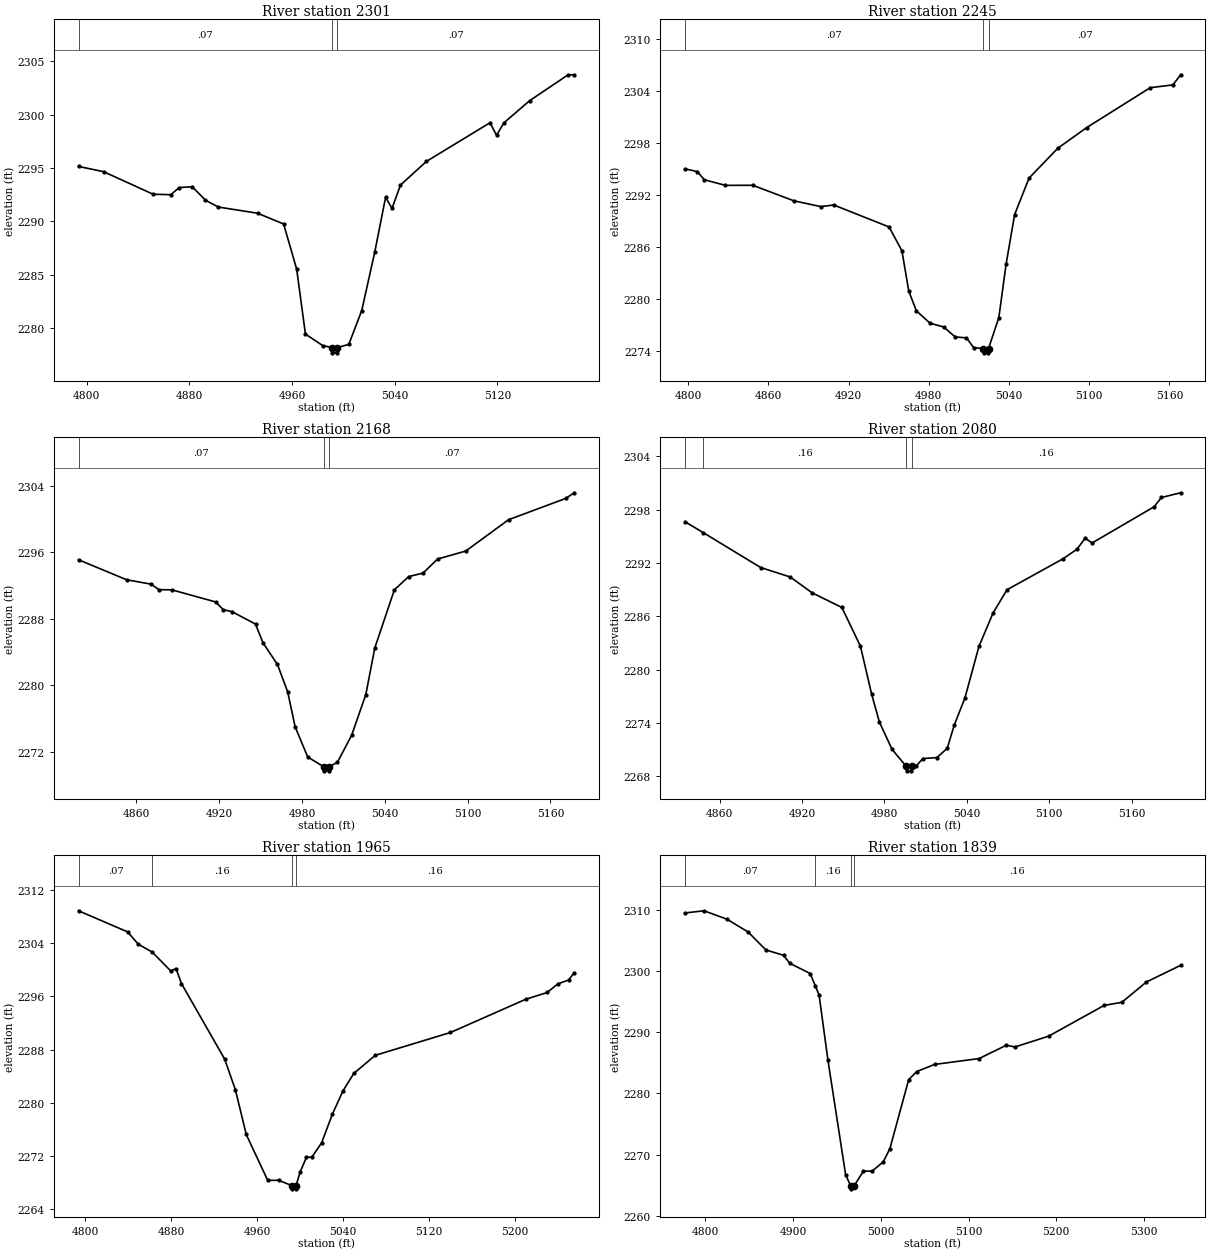
Type RM Length L Ch R = 1,2301,56,56,56
BEGIN DESCRIPTION:
elmc782
END DESCRIPTION:
XS GIS Cut Line= 3
      1502497.84      6764599.94      1502698.37      6764637.70
      1502879.36      6764615.57
#Sta/Elev= 30
  4793.5 2295.14  4813.0 2294.65  4851.7 2292.53  4865.5 2292.49  4872.0 2293.16
  4882.2 2293.23  4892.4 2291.98  4902.5 2291.33  4933.1 2290.75  4953.4 2289.74
  4963.6 2285.49  4970.4 2279.41  4984.0 2278.32  4991.3 2278.15  4991.5 2277.65
  4995.0 2277.65  4995.3 2278.15  5004.2 2278.44  5014.3 2281.62  5024.4 2287.08
  5032.9 2292.25  5037.9 2291.20  5044.5 2293.39  5064.7 2295.61  5114.3 2299.24
  5119.4 2298.06  5125.1 2299.23  5145.3 2301.32  5175.2 2303.74  5179.9 2303.74
#Mann=3,-1,0
  4793.5    0.07       0  4991.3    0.07       0  4995.3    0.07       0
Bank Sta=4991.3,4995.3
Exp/Cntr=0.3,0.1

Type RM Length L Ch R = 1,2245,77,77,77
BEGIN DESCRIPTION:
elmc781
END DESCRIPTION:
XS GIS Cut Line= 3
      1502465.25      6764640.30      1502667.12      6764680.67
      1502820.35      6764741.70
#Sta/Elev= 30
  4797.6 2295.03  4806.9 2294.71  4812.0 2293.77  4827.9 2293.12  4848.3 2293.13
  4878.9 2291.34  4899.3 2290.66  4908.9 2290.85  4950.3 2288.31  4959.9 2285.55
  4965.0 2280.90  4970.7 2278.61  4980.9 2277.18  4991.1 2276.74  4999.8 2275.59
  5008.2 2275.48  5013.5 2274.36  5020.7 2274.25  5021.0 2273.75  5024.5 2273.75
  5024.7 2274.25  5032.4 2277.83  5037.8 2283.98  5044.2 2289.74  5055.0 2293.96
  5076.5 2297.41  5098.1 2299.80  5145.7 2304.42  5162.6 2304.74  5168.4 2305.91
#Mann=3,-1,0
  4797.6    0.07       0  5020.7    0.07       0  5024.7    0.07       0
Bank Sta=5020.7,5024.7
Exp/Cntr=0.3,0.1

Type RM Length L Ch R = 1,2168,88,88,88
BEGIN DESCRIPTION:
elmc780
END DESCRIPTION:
XS GIS Cut Line= 3
      1502443.13      6764661.13      1502608.52      6764734.06
      1502780.89      6764779.42
#Sta/Elev= 30
  4818.2 2295.08  4853.1 2292.67  4870.9 2292.14  4876.4 2291.48  4885.8 2291.46
  4917.6 2290.00  4923.0 2289.08  4929.5 2288.82  4946.4 2287.34  4951.8 2285.09
  4962.3 2282.48  4969.7 2279.18  4975.1 2274.98  4984.2 2271.35  4995.7 2270.18
  4995.9 2269.68  4999.4 2269.68  4999.7 2270.18  5005.7 2270.70  5016.0 2273.95
  5026.3 2278.86  5032.8 2284.47  5047.0 2291.47  5057.4 2293.06  5067.7 2293.47
  5078.3 2295.17  5098.7 2296.13  5129.7 2299.90  5171.1 2302.46  5177.2 2303.14
#Mann=3,-1,0
  4818.2    0.07       0  4995.7    0.07       0  4999.7    0.07       0
Bank Sta=4995.7,4999.7
Exp/Cntr=0.3,0.1

Type RM Length L Ch R = 1,2080,115,115,115
BEGIN DESCRIPTION:
elmc779
END DESCRIPTION:
XS GIS Cut Line= 3
      1502404.09      6764714.52      1502549.93      6764797.86
      1502738.75      6764836.93
#Sta/Elev= 30
  4834.8 2296.63  4848.0 2295.41  4889.9 2291.48  4911.5 2290.41  4927.4 2288.63
  4949.0 2286.99  4962.5 2282.65  4970.6 2277.29  4976.3 2274.12  4985.6 2271.03
  4995.9 2269.13  4996.1 2268.63  4999.6 2268.63  4999.9 2269.13  5002.8 2269.13
  5008.0 2270.01  5018.2 2270.12  5025.7 2271.16  5030.8 2273.76  5038.6 2276.83
  5048.8 2282.62  5059.0 2286.35  5069.2 2288.98  5110.1 2292.47  5120.3 2293.56
  5126.1 2294.78  5131.2 2294.24  5176.3 2298.31  5181.6 2299.35  5195.6 2299.88
#Mann=4,-1,0
  4834.8    0.07       0  4848.0    0.16       0  4995.9    0.07       0
  4999.9    0.16       0
Bank Sta=4995.9,4999.9
Exp/Cntr=0.3,0.1

Type RM Length L Ch R = 1,1965,126,126,126
BEGIN DESCRIPTION:
elmc778
END DESCRIPTION:
XS GIS Cut Line= 3
      1502289.50      6764874.68      1502501.75      6764894.21
      1502750.20      6764895.51
#Sta/Elev= 30
  4793.8 2308.92  4839.5 2305.74  4849.5 2303.88  4862.6 2302.67  4879.6 2299.86
  4884.6 2300.20  4889.7 2297.94  4929.9 2286.56  4939.9 2281.94  4950.0 2275.20
  4970.0 2268.28  4980.1 2268.29  4992.4 2267.50  4992.7 2267.00  4996.2 2267.00
  4996.4 2267.50  5000.2 2269.52  5006.1 2271.78  5011.1 2271.78  5020.2 2273.93
  5030.2 2278.25  5040.2 2281.80  5050.2 2284.40  5070.2 2287.13  5140.2 2290.57
  5210.2 2295.57  5230.2 2296.60  5240.2 2297.90  5250.2 2298.48  5255.4 2299.57
#Mann=4,-1,0
  4793.8    0.07       0  4862.6    0.16       0  4992.4    0.07       0
  4996.4    0.16       0
Bank Sta=4992.4,4996.4
Exp/Cntr=0.3,0.1

Type RM Length L Ch R = 1,1839,77,77,77
BEGIN DESCRIPTION:
elmc775
END DESCRIPTION:
XS GIS Cut Line= 3
      1502233.55      6764976.25      1502457.48      6765007.49
      1502791.05      6764946.49
#Sta/Elev= 30
  4776.6 2309.49  4798.3 2309.85  4824.5 2308.47  4848.7 2306.37  4868.9 2303.44
  4889.1 2302.57  4896.0 2301.27  4919.4 2299.59  4925.3 2297.55  4929.5 2296.09
  4939.6 2285.45  4959.8 2266.68  4965.5 2264.89  4965.8 2264.39  4969.5 2264.89
  4980.0 2267.27  4990.1 2267.30  5002.7 2268.80  5010.3 2270.98  5031.7 2282.24
  5040.8 2283.56  5061.2 2284.73  5112.0 2285.69  5143.2 2287.88  5152.7 2287.58
  5191.3 2289.35  5254.7 2294.39  5274.7 2294.88  5302.8 2298.21  5341.8 2300.93
#Mann=4,-1,0
  4776.6    0.07       0  4925.3    0.16       0  4965.5    0.07       0
  4969.5    0.16       0
Bank Sta=4965.5,4969.5
Exp/Cntr=0.3,0.1

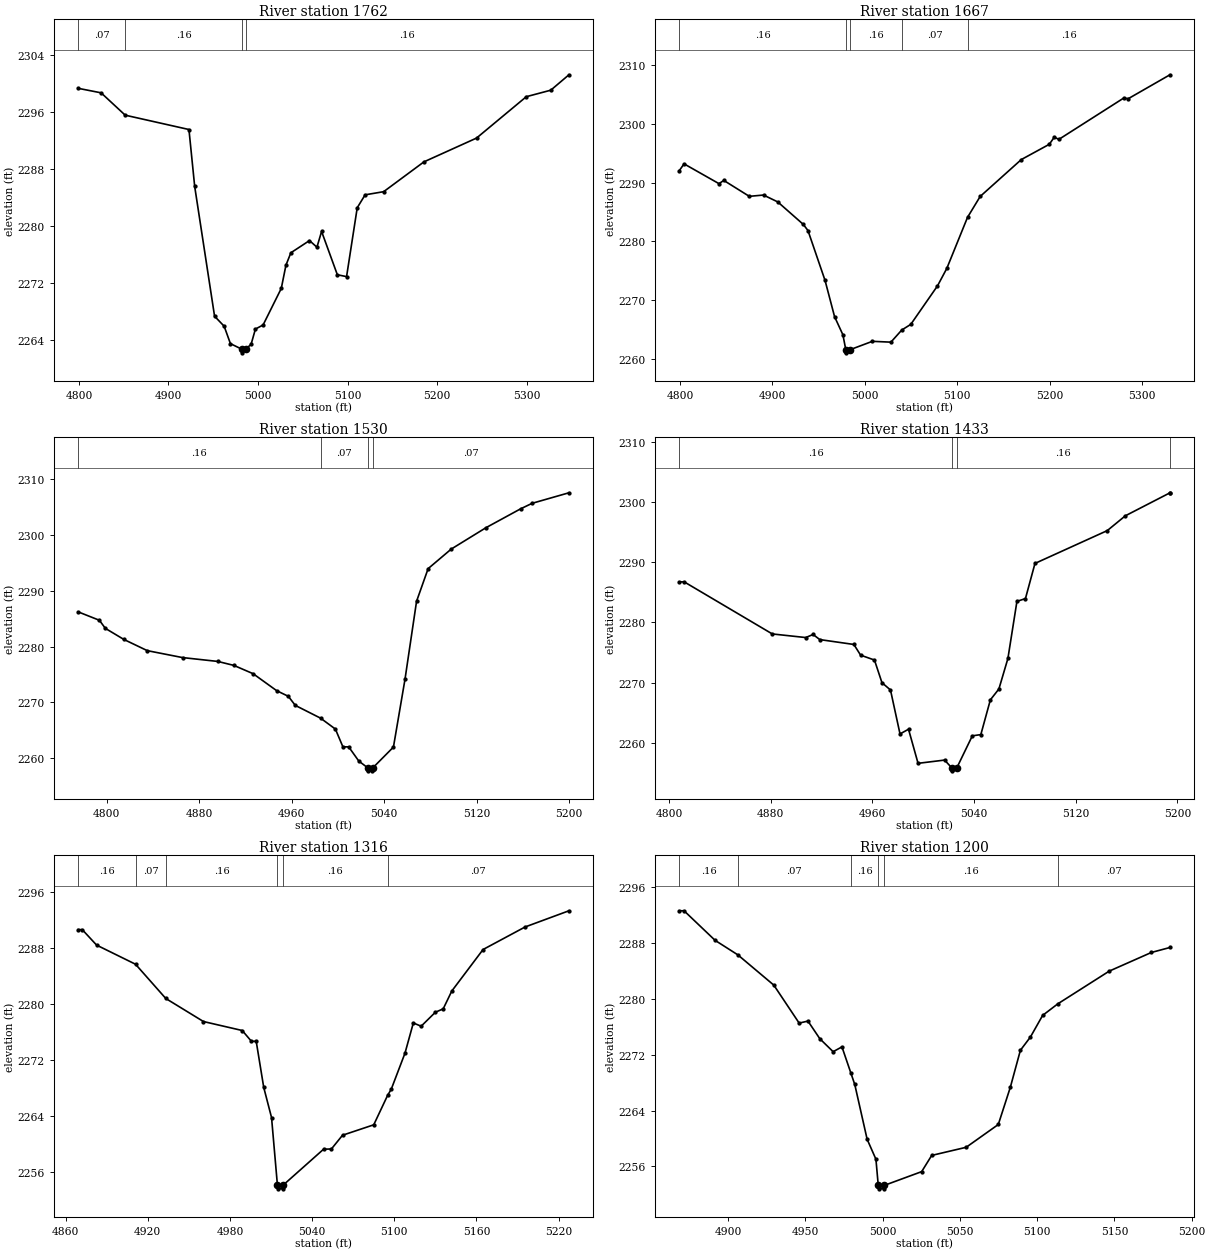
Type RM Length L Ch R = 1,1762,95,95,95
BEGIN DESCRIPTION:
elmc776
END DESCRIPTION:
XS GIS Cut Line= 3
      1502306.47      6765153.31      1502488.73      6765071.30
      1502824.62      6764980.16
#Sta/Elev= 30
  4799.3 2299.26  4824.8 2298.63  4851.7 2295.50  4922.9 2293.49  4929.3 2285.51
  4951.5 2267.33  4962.2 2265.93  4969.2 2263.49  4982.1 2262.70  4982.4 2262.20
  4986.1 2262.70  4992.3 2263.40  4997.1 2265.53  5005.7 2266.11  5026.0 2271.23
  5031.2 2274.48  5036.7 2276.22  5057.5 2277.93  5065.8 2277.00  5071.0 2279.21
  5088.6 2273.14  5098.9 2272.88  5110.8 2282.53  5119.6 2284.34  5140.3 2284.78
  5185.3 2288.96  5244.0 2292.29  5299.6 2298.09  5326.9 2299.00  5347.2 2301.16
#Mann=4,-1,0
  4799.3    0.07       0  4851.7    0.16       0  4982.1    0.07       0
  4986.1    0.16       0
Bank Sta=4982.1,4986.1
Exp/Cntr=0.3,0.1

Type RM Length L Ch R = 1,1667,137,137,137
BEGIN DESCRIPTION:
elmc777
END DESCRIPTION:
XS GIS Cut Line= 3
      1502361.11      6765183.28      1502555.14      6765139.00
      1502884.60      6765097.33
#Sta/Elev= 30
  4799.2 2292.02  4804.4 2293.18  4842.2 2289.81  4847.4 2290.36  4875.0 2287.65
  4890.4 2287.87  4905.8 2286.70  4933.4 2282.88  4938.5 2281.83  4957.0 2273.33
  4967.3 2267.16  4976.3 2264.08  4979.5 2261.50  4979.7 2261.00  4983.5 2261.50
  5008.2 2262.96  5028.3 2262.82  5040.0 2264.88  5049.8 2265.85  5078.7 2272.40
  5088.8 2275.38  5111.2 2284.07  5124.9 2287.63  5169.4 2293.91  5199.7 2296.51
  5205.1 2297.72  5210.1 2297.35  5280.2 2304.38  5285.2 2304.28  5330.3 2308.35
#Mann=5,-1,0
  4799.2    0.16       0  4979.5    0.07       0  4983.5    0.16       0
  5040.0    0.07       0  5111.2    0.16       0
Bank Sta=4979.5,4983.5
Exp/Cntr=0.3,0.1

Type RM Length L Ch R = 1,1530,97,97,97
BEGIN DESCRIPTION:
elmc772
END DESCRIPTION:
XS GIS Cut Line= 3
      1502426.25      6765198.90      1502652.79      6765240.57
      1502846.81      6765236.66
#Sta/Elev= 30
  4775.3 2286.20  4793.6 2284.70  4798.7 2283.26  4814.7 2281.28  4835.0 2279.27
  4865.5 2278.03  4896.0 2277.34  4909.9 2276.63  4926.5 2275.15  4946.9 2272.11
  4957.0 2271.10  4963.0 2269.48  4984.9 2267.19  4997.7 2265.24  5004.2 2262.06
  5009.2 2262.06  5017.9 2259.53  5025.9 2258.27  5026.1 2257.77  5029.6 2257.77
  5029.9 2258.27  5047.9 2262.02  5057.9 2274.15  5067.9 2288.10  5077.9 2293.94
  5097.9 2297.44  5127.9 2301.26  5157.9 2304.64  5167.9 2305.63  5199.7 2307.51
#Mann=4,-1,0
  4775.3    0.16       0  4984.9    0.07       0  5025.9    0.07       0
  5029.9    0.07       0
Bank Sta=5025.9,5029.9
Exp/Cntr=0.3,0.1

Type RM Length L Ch R = 1,1433,117,117,117
BEGIN DESCRIPTION:
elmc774
END DESCRIPTION:
XS GIS Cut Line= 3
      1502400.22      6765210.63      1502542.12      6765256.19
      1502699.78      6765433.24
#Sta/Elev= 30
  4808.1 2286.74  4812.0 2286.74  4881.3 2278.08  4907.6 2277.48  4913.4 2277.99
  4918.7 2277.14  4945.5 2276.33  4950.8 2274.55  4961.7 2273.74  4967.6 2269.97
  4974.3 2268.76  4981.8 2261.45  4988.5 2262.23  4996.0 2256.56  5016.9 2257.10
  5022.5 2255.81  5022.7 2255.31  5026.5 2255.81  5038.7 2261.13  5045.4 2261.34
  5052.9 2267.12  5059.6 2268.92  5066.7 2274.00  5073.8 2283.50  5080.5 2283.96
  5088.0 2289.81  5144.9 2295.27  5159.1 2297.73  5194.0 2301.53  5194.2 2301.56
#Mann=4,-1,0
  4808.1    0.16       0  5022.5    0.07       0  5026.5    0.16       0
  5194.0    0.07       0
Bank Sta=5022.5,5026.5
Exp/Cntr=0.3,0.1

Type RM Length L Ch R = 1,1316,116,116,116
BEGIN DESCRIPTION:
elmc773
END DESCRIPTION:
XS GIS Cut Line= 3
      1502365.00      6765198.87      1502454.88      6765292.65
      1502564.20      6765493.08
#Sta/Elev= 30
  4869.3 2290.65  4872.2 2290.65  4882.7 2288.44  4911.1 2285.71  4933.2 2280.82
  4960.7 2277.53  4989.0 2276.25  4995.7 2274.71  4999.2 2274.71  5004.7 2268.12
  5010.4 2263.82  5014.7 2254.15  5014.9 2253.65  5018.4 2253.65  5018.7 2254.15
  5048.4 2259.31  5054.1 2259.34  5062.2 2261.30  5085.0 2262.79  5095.1 2266.98
  5097.8 2267.88  5107.8 2273.01  5113.9 2277.33  5119.6 2276.86  5130.0 2278.86
  5135.7 2279.34  5142.0 2281.89  5164.8 2287.81  5195.5 2291.03  5227.5 2293.34
#Mann=6,-1,0
  4869.3    0.16       0  4911.1    0.07       0  4933.2    0.16       0
  5014.7    0.07       0  5018.7    0.16       0  5095.1    0.07       0
Bank Sta=5014.7,5018.7
Exp/Cntr=0.3,0.1

Type RM Length L Ch R = 1,1200,158,158,158
BEGIN DESCRIPTION:
elmc771
END DESCRIPTION:
XS GIS Cut Line= 3
      1502292.10      6765227.52      1502353.31      6765343.43
      1502470.93      6765488.19
#Sta/Elev= 30
  4868.3 2292.56  4871.4 2292.56  4891.5 2288.33  4906.2 2286.26  4929.5 2281.93
  4945.9 2276.50  4951.6 2276.79  4959.3 2274.26  4967.9 2272.41  4973.6 2273.10
  4979.3 2269.41  4981.9 2267.72  4989.9 2259.89  4995.6 2257.03  4997.1 2253.30
  4997.4 2252.80  5000.9 2252.80  5001.1 2253.30  5025.2 2255.26  5031.7 2257.58
  5054.0 2258.74  5074.8 2262.00  5082.6 2267.33  5089.1 2272.61  5095.6 2274.51
  5103.5 2277.60  5113.3 2279.25  5146.6 2283.93  5173.9 2286.60  5185.9 2287.31
#Mann=6,-1,0
  4868.3    0.16       0  4906.2    0.07       0  4979.3    0.16       0
  4997.1    0.07       0  5001.1    0.16       0  5113.3    0.07       0
Bank Sta=4997.1,5001.1
Exp/Cntr=0.3,0.1

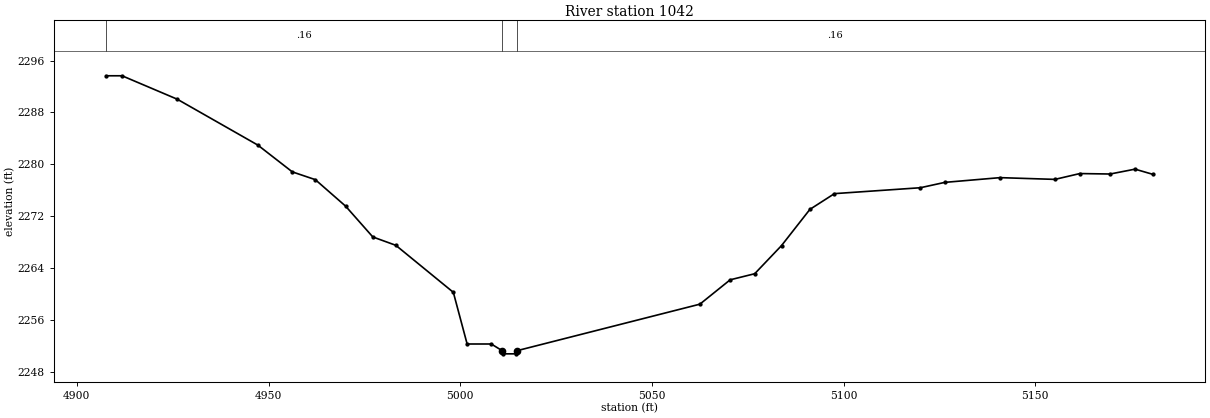
Type RM Length L Ch R = 1,1042,153,153,153
BEGIN DESCRIPTION:
elmc770
END DESCRIPTION:
XS GIS Cut Line= 3
      1502160.60      6765316.09      1502213.99      6765395.51
      1502325.76      6765533.28
#Sta/Elev= 30
  4907.6 2293.67  4911.8 2293.67  4926.2 2290.05  4947.2 2282.97  4956.2 2278.83
  4962.2 2277.63  4970.1 2273.54  4977.2 2268.78  4983.2 2267.49  4998.2 2260.23
  5001.8 2252.25  5008.1 2252.25  5010.9 2251.23  5011.1 2250.73  5014.6 2250.73
  5014.9 2251.23  5062.5 2258.40  5070.4 2262.16  5076.8 2263.10  5083.8 2267.45
  5091.2 2273.04  5097.6 2275.47  5120.0 2276.38  5126.4 2277.21  5140.8 2277.94
  5155.1 2277.67  5161.6 2278.57  5169.5 2278.50  5176.0 2279.25  5180.7 2278.44
#Mann=3,-1,0
  4907.6    0.16       0  5010.9    0.07       0  5014.9    0.16       0
Bank Sta=5010.9,5014.9
Exp/Cntr=0.3,0.1