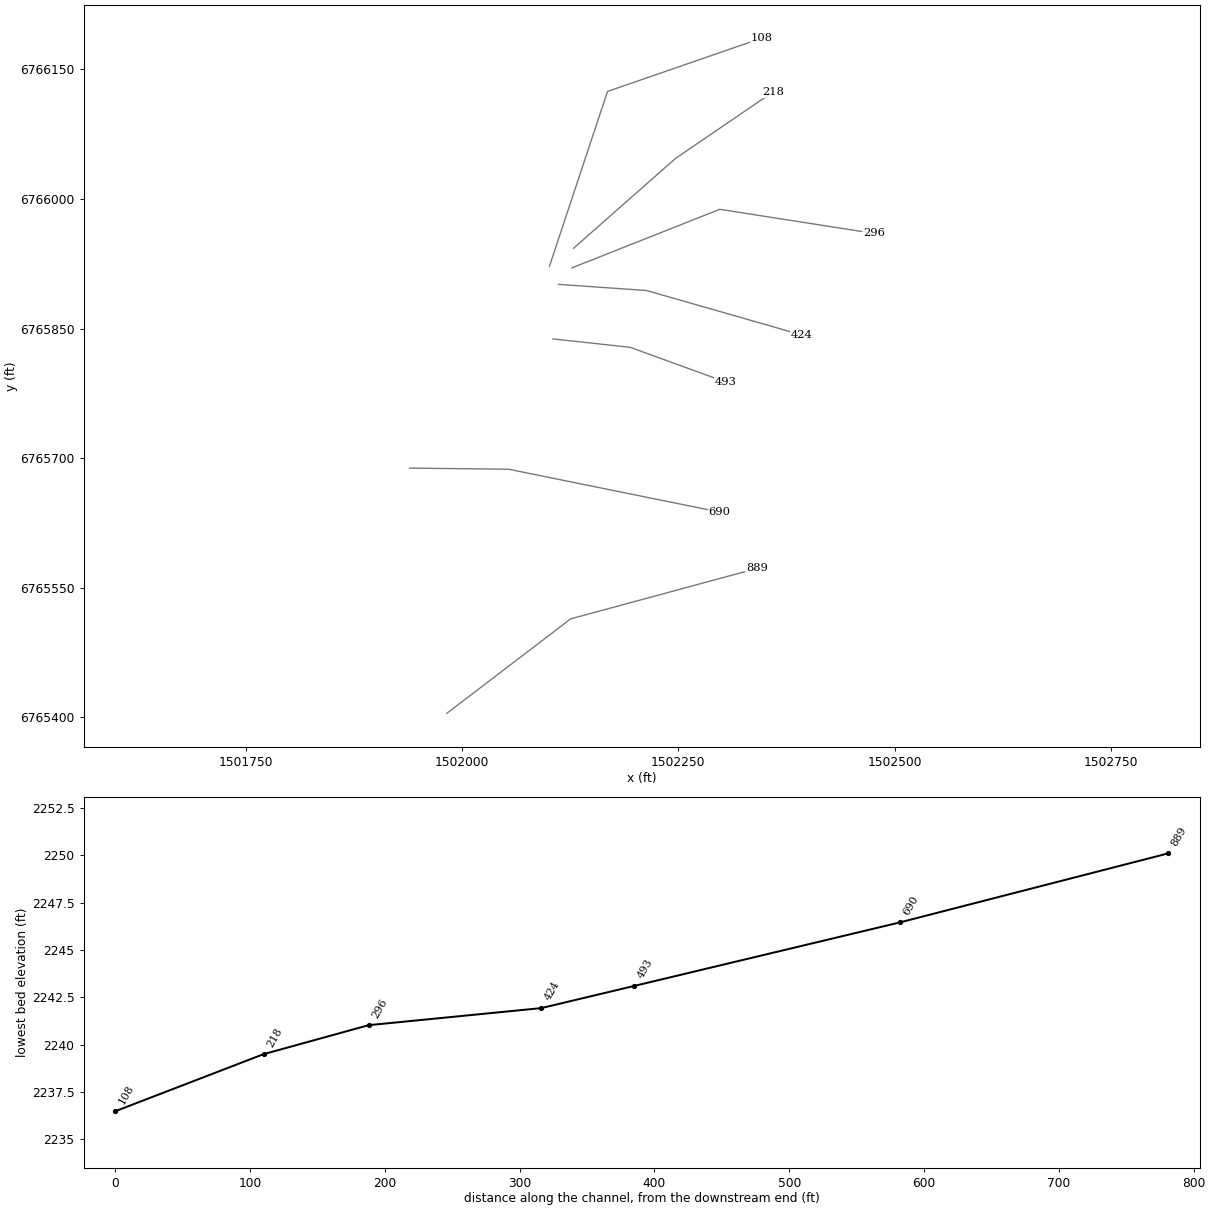
HEC-RAS study Elm 36.prj: Elm 36 Base Level Engineering

--- Elm 36.g01 (geometry) --- (continued)

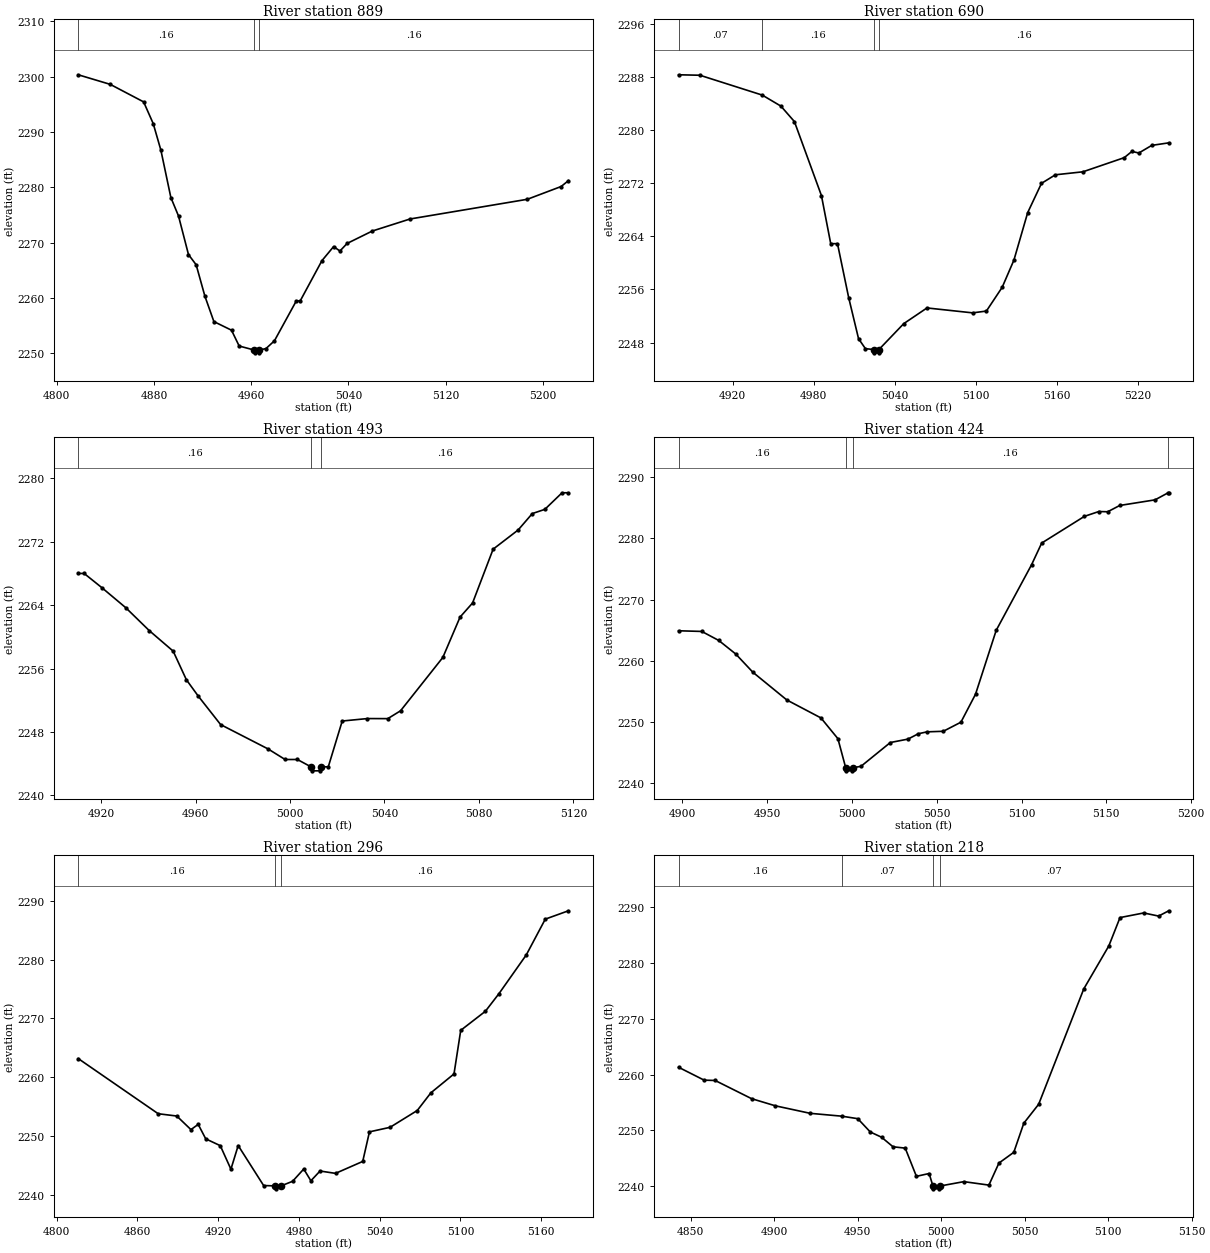
Type RM Length L Ch R = 1,889,199,199,199
BEGIN DESCRIPTION:
elmc769
END DESCRIPTION:
XS GIS Cut Line= 3
      1501982.22      6765404.63      1502125.45      6765514.00
      1502340.76      6765572.37
#Sta/Elev= 30
  4817.7 2300.34  4844.0 2298.61  4871.5 2295.44  4879.4 2291.51  4885.7 2286.71
  4893.9 2278.16  4900.2 2274.82  4908.4 2267.85  4914.7 2266.01  4921.9 2260.33
  4929.3 2255.74  4943.8 2254.18  4950.1 2251.32  4962.6 2250.59  4962.9 2250.09
  4966.4 2250.09  4966.6 2250.59  4972.2 2250.87  4979.1 2252.26  4997.1 2259.47
  5000.3 2259.47  5018.2 2266.75  5027.8 2269.29  5033.0 2268.49  5038.9 2269.86
  5059.6 2272.10  5090.7 2274.28  5187.2 2277.84  5215.0 2280.15  5221.0 2281.21
#Mann=3,-1,0
  4817.7    0.16       0  4962.6    0.07       0  4966.6    0.16       0
Bank Sta=4962.6,4966.6
Exp/Cntr=0.3,0.1

Type RM Length L Ch R = 1,690,197,197,197
BEGIN DESCRIPTION:
elmc768
END DESCRIPTION:
XS GIS Cut Line= 3
      1501939.25      6765688.48      1502053.83      6765687.18
      1502297.36      6765637.69
#Sta/Elev= 30
  4880.0 2288.32  4895.8 2288.25  4942.0 2285.26  4955.8 2283.60  4965.8 2281.27
  4985.8 2270.14  4992.7 2262.89  4997.7 2262.89  5006.0 2254.76  5013.3 2248.58
  5018.4 2247.08  5024.4 2246.95  5024.6 2246.45  5028.1 2246.45  5028.4 2246.95
  5046.8 2250.85  5064.0 2253.21  5097.8 2252.47  5108.0 2252.74  5119.7 2256.32
  5128.4 2260.42  5138.6 2267.57  5148.8 2271.97  5159.1 2273.26  5179.5 2273.71
  5210.1 2275.84  5215.8 2276.78  5220.9 2276.54  5230.5 2277.69  5243.1 2278.07
#Mann=4,-1,0
  4880.0    0.07       0  4942.0    0.16       0  5024.4    0.07       0
  5028.4    0.16       0
Bank Sta=5024.4,5028.4
Exp/Cntr=0.3,0.1

Type RM Length L Ch R = 1,493,69,69,69
BEGIN DESCRIPTION:
elmc373
END DESCRIPTION:
XS GIS Cut Line= 3
      1502105.04      6765838.00      1502194.22      6765828.32
      1502305.01      6765788.00
#Sta/Elev= 30
  4910.3 2267.98  4912.8 2267.98  4920.3 2266.19  4930.4 2263.67  4940.4 2260.77
  4950.5 2258.19  4956.1 2254.58  4961.1 2252.53  4970.6 2248.93  4990.7 2245.86
  4997.9 2244.53  5003.1 2244.53  5008.9 2243.60  5009.1 2243.10  5012.6 2243.10
  5012.9 2243.60  5016.2 2243.61  5022.1 2249.38  5032.8 2249.69  5041.4 2249.68
  5046.8 2250.67  5064.7 2257.39  5072.0 2262.48  5077.3 2264.26  5086.0 2271.04
  5096.6 2273.46  5102.6 2275.53  5107.9 2276.06  5115.2 2278.15  5117.9 2278.15
#Mann=3,-1,0
  4910.3    0.16       0  5008.9    0.07       0  5012.9    0.16       0
Bank Sta=5008.9,5012.9
Exp/Cntr=0.3,0.1

Type RM Length L Ch R = 1,424,128,128,128
BEGIN DESCRIPTION:
elmc767
END DESCRIPTION:
XS GIS Cut Line= 3
      1502111.35      6765901.16      1502213.20      6765894.05
      1502392.77      6765842.58
#Sta/Elev= 30
  4897.9 2264.88  4911.6 2264.77  4921.6 2263.29  4931.6 2261.07  4941.7 2258.08
  4961.7 2253.54  4981.8 2250.60  4991.8 2247.20  4996.4 2242.43  4996.6 2241.93
  5000.1 2241.93  5000.4 2242.43  5005.4 2242.67  5022.7 2246.57  5033.1 2247.13
  5039.2 2248.01  5044.4 2248.32  5053.9 2248.41  5064.3 2249.90  5072.9 2254.48
  5085.1 2264.96  5105.9 2275.68  5111.9 2279.25  5137.1 2283.63  5145.6 2284.42
  5150.8 2284.38  5157.9 2285.41  5178.7 2286.33  5186.3 2287.47  5186.8 2287.49
#Mann=4,-1,0
  4897.9    0.16       0  4996.4    0.07       0  5000.4    0.16       0
  5186.3    0.07       0
Bank Sta=4996.4,5000.4
Exp/Cntr=0.3,0.1

Type RM Length L Ch R = 1,296,78,78,78
BEGIN DESCRIPTION:
elmc766
END DESCRIPTION:
XS GIS Cut Line= 3
      1502126.95      6765920.25      1502297.92      6765988.00
      1502475.96      6765960.18
#Sta/Elev= 30
  4816.1 2263.18  4875.5 2253.80  4889.3 2253.41  4899.8 2251.10  4905.2 2251.99
  4910.8 2249.53  4921.6 2248.37  4929.5 2244.37  4934.9 2248.39  4953.8 2241.59
  4962.6 2241.53  4962.8 2241.03  4966.7 2241.53  4975.3 2242.31  4983.6 2244.40
  4988.9 2242.40  4995.7 2244.06  5007.2 2243.66  5027.4 2245.69  5032.4 2250.72
  5047.7 2251.49  5067.9 2254.35  5078.0 2257.35  5095.2 2260.57  5100.2 2267.98
  5118.5 2271.22  5128.6 2274.22  5148.9 2280.81  5163.0 2286.89  5180.2 2288.31
#Mann=3,-1,0
  4816.1    0.16       0  4962.6    0.07       0  4966.7    0.16       0
Bank Sta=4962.6,4966.7
Exp/Cntr=0.3,0.1

Type RM Length L Ch R = 1,218,110,110,110
BEGIN DESCRIPTION:
elmc765
END DESCRIPTION:
XS GIS Cut Line= 3
      1502128.68      6765942.80      1502246.57      6766046.78
      1502359.15      6766123.62
#Sta/Elev= 30
  4842.8 2261.30  4858.1 2258.99  4864.7 2258.93  4886.5 2255.67  4900.7 2254.39
  4921.6 2253.04  4940.5 2252.53  4950.1 2252.08  4957.6 2249.69  4964.3 2248.76
  4971.2 2247.04  4978.5 2246.80  4985.2 2241.74  4992.8 2242.25  4995.1 2240.00
  4995.3 2239.50  4998.9 2239.50  4999.2 2240.00  5013.6 2240.79  5028.6 2240.17
  5034.6 2244.12  5043.5 2246.05  5049.5 2251.27  5058.4 2254.67  5085.4 2275.35
  5100.4 2283.06  5107.1 2288.14  5121.3 2288.97  5130.2 2288.41  5136.3 2289.36
#Mann=4,-1,0
  4842.8    0.16       0  4940.5    0.07       0  4995.1    0.07       0
  4999.2    0.07       0
Bank Sta=4995.1,4999.2
Exp/Cntr=0.3,0.1

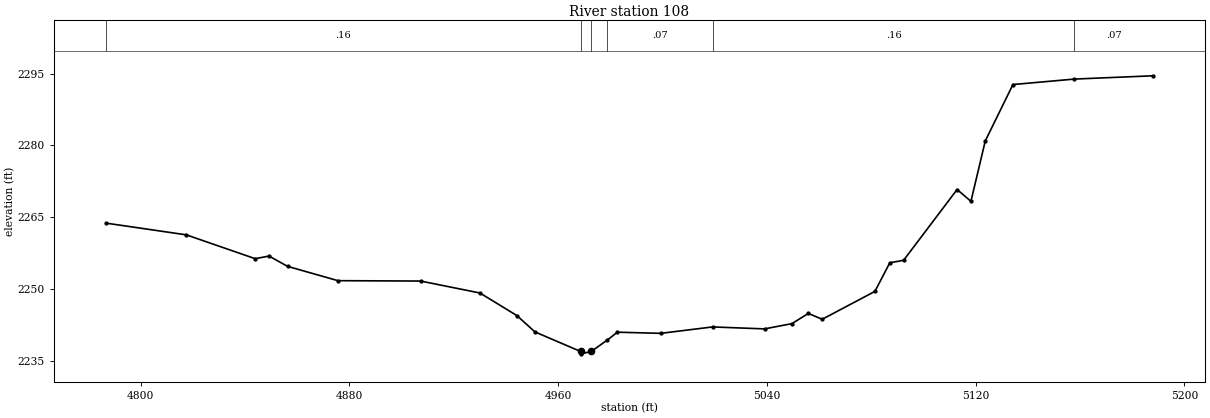
Type RM Length L Ch R = 1,108,0,0,0
BEGIN DESCRIPTION:
elmc764
END DESCRIPTION:
XS GIS Cut Line= 3
      1502100.91      6765921.95      1502168.08      6766124.40
      1502345.74      6766185.89
#Sta/Elev= 30
  4786.7 2263.79  4817.5 2261.34  4843.9 2256.36  4849.2 2256.91  4856.3 2254.76
  4875.6 2251.77  4907.3 2251.69  4930.0 2249.20  4944.2 2244.48  4951.1 2241.07
  4968.6 2236.99  4968.8 2236.49  4972.7 2236.99  4978.8 2239.36  4982.7 2241.01
  4999.3 2240.77  5019.2 2242.11  5039.1 2241.70  5049.6 2242.80  5055.9 2244.93
  5061.2 2243.71  5081.4 2249.53  5087.1 2255.50  5092.4 2256.03  5112.9 2270.81
  5118.2 2268.34  5123.7 2280.96  5134.3 2292.73  5157.8 2293.87  5188.0 2294.56
#Mann=6,-1,0
  4786.7    0.16       0  4968.6    0.07       0  4972.7    0.16       0
  4978.8    0.07       0  5019.2    0.16       0  5157.8    0.07       0
Bank Sta=4968.6,4972.7
Exp/Cntr=0.3,0.1

Chan Stop Cuts=-1