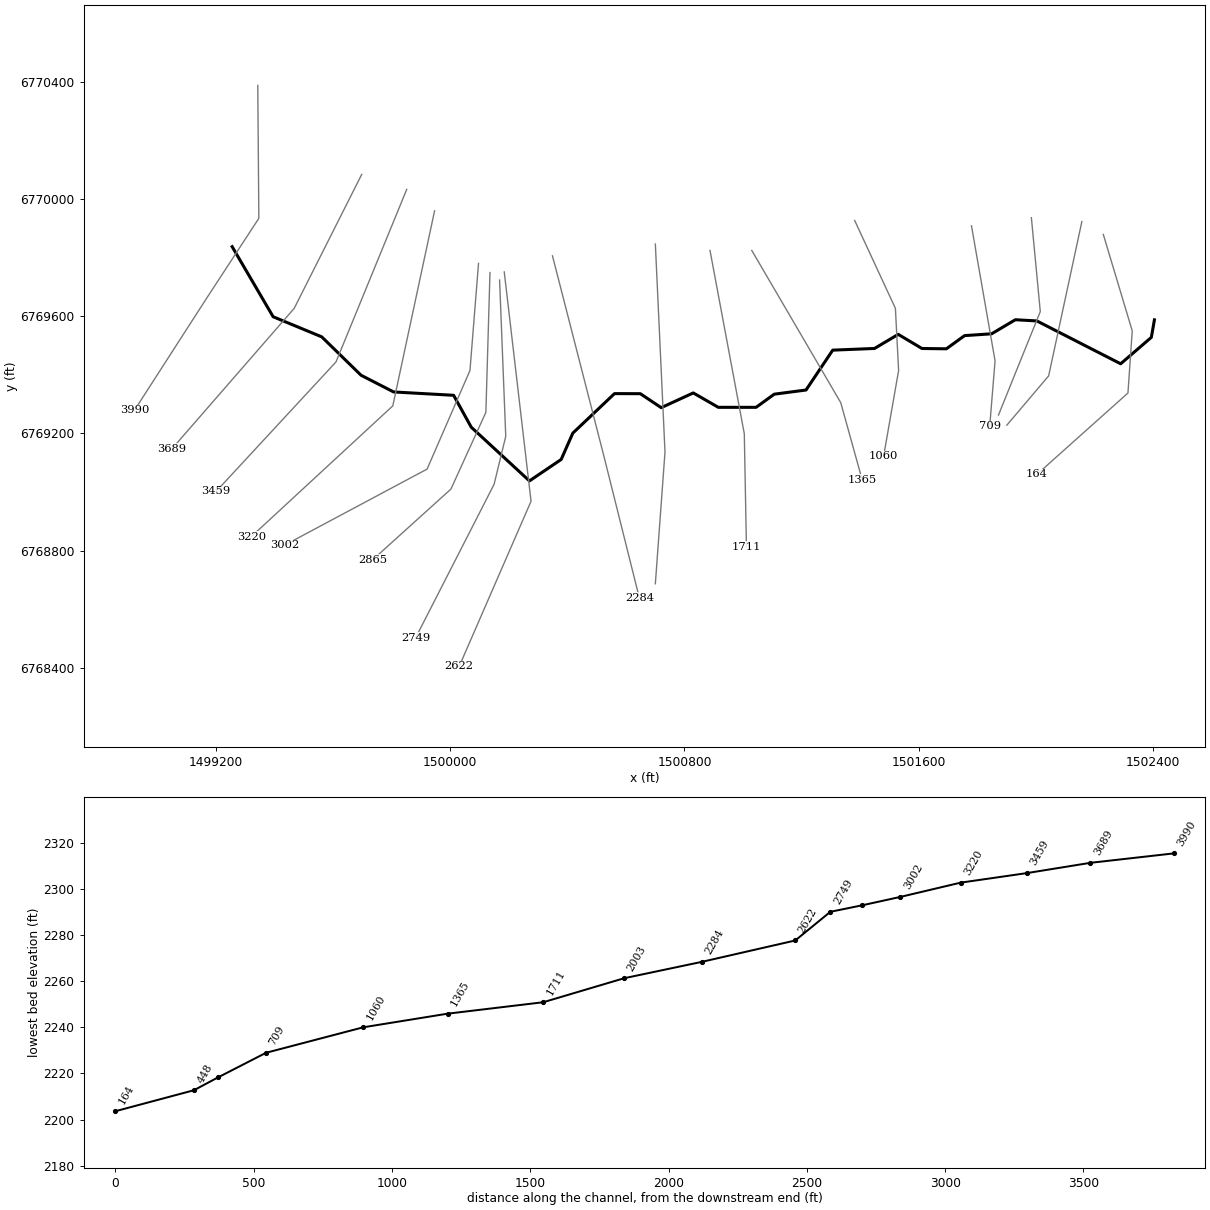
--- Elm 37.prj (project) ---

Proj Title=Elm 37 Base Level Engineering
Current Plan=p01
Default Exp/Contr=0.3,0.1
English Units
Geom File=g01
Flow File=f01
Plan File=p01
BEGIN DESCRIPTION:
Elm 37
END DESCRIPTION:

--- Elm 37.p01 (plan) ---

Plan Title=Multiple Run
Short Identifier=Multiple
Geom File=g01
Flow File=f01
Subcritical Flow
K Sum by GR= 0
Std Step Tol= 0.01
Critical Tol= 0.01
Num of Std Step Trials= 20
Max Error Tol= 0.3
Flow Tol Ratio= 0.001
Split Flow NTrial= 30
Split Flow Tol= 0.02
Split Flow Ratio= 0.02
Log Output Level= 0
Friction Slope Method= 1
Unsteady Friction Slope Method= 2
Unsteady Bridges Friction Slope Method= 1
Parabolic Critical Depth
Global Vel Dist=  1 , 1 , 1
Global Log Level= 0
CheckData=True
Encroach Param= -1, 0, 0, 0
BEGIN DESCRIPTION:
Multiple Run
END DESCRIPTION:

--- Elm 37.f01 (steady flow) ---

Flow Title=Multiple
Number of Profiles=7
Profile Names=10-year,25-year,50-year,1pct_min,100-year,1pct_plu,500-year
River Rch & RM= Elm 37,Reach-1,3990
     140     190     230     174     278     383     410
Boundary for River Rch & Prof#=Elm 37,Reach-1,1
Up Type=0
Dn Type=3
Dn Slope=0.005
Boundary for River Rch & Prof#=Elm 37,Reach-1,2
Up Type=0
Dn Type=3
Dn Slope=0.005
Boundary for River Rch & Prof#=Elm 37,Reach-1,3
Up Type=0
Dn Type=3
Dn Slope=0.005
Boundary for River Rch & Prof#=Elm 37,Reach-1,4
Up Type=0
Dn Type=3
Dn Slope=0.005
Boundary for River Rch & Prof#=Elm 37,Reach-1,5
Up Type=0
Dn Type=3
Dn Slope=0.005
Boundary for River Rch & Prof#=Elm 37,Reach-1,6
Up Type=0
Dn Type=3
Dn Slope=0.005
Boundary for River Rch & Prof#=Elm 37,Reach-1,7
Up Type=0
Dn Type=3
Dn Slope=0.005

--- Elm 37.g01 (geometry) ---

Geom Title=Existing Conditions

River Reach=Elm 37,Reach-1
Reach XY= 30
      1499255.00      6769838.00      1499395.00      6769598.63
      1499561.06      6769529.86      1499695.32      6769398.76
      1499806.55      6769341.75      1500011.48      6769330.31
      1500071.66      6769221.34      1500270.36      6769037.89
      1500378.73      6769111.11      1500418.63      6769201.21
      1500560.89      6769336.04      1500649.03      6769335.81
      1500720.40      6769288.10      1500830.00      6769338.39
      1500915.50      6769289.23      1501044.49      6769289.20
      1501106.60      6769334.14      1501215.10      6769348.39
      1501306.25      6769484.54      1501449.07      6769490.30
      1501530.00      6769538.40      1501610.97      6769490.19
      1501694.45      6769489.10      1501756.60      6769534.14
      1501849.03      6769540.36      1501930.00      6769588.40
      1502003.42      6769584.33      1502289.67      6769437.94
      1502394.50      6769528.18      1502405.00      6769588.00

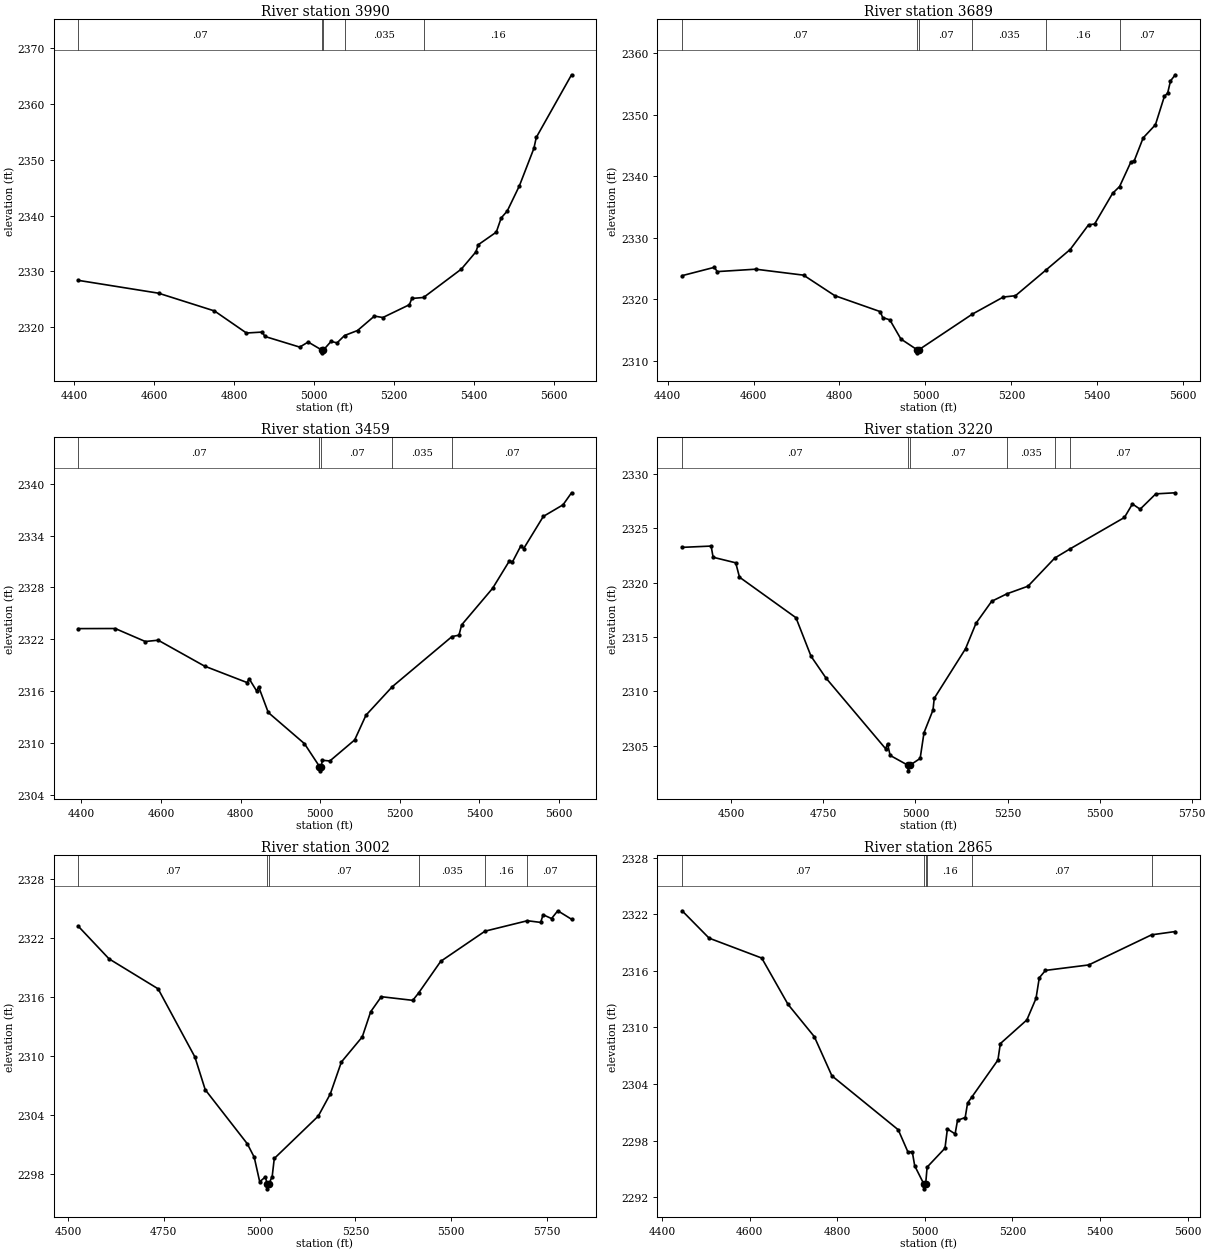
Type RM Length L Ch R = 1,3990,301,301,301
BEGIN DESCRIPTION:
elmc313
END DESCRIPTION:
XS GIS Cut Line= 4
      1499342.53      6770388.64      1499346.19      6769934.74
      1499166.84      6769660.23      1498921.63      6769279.60
#Sta/Elev= 30
  4410.5 2328.37  4611.1 2326.07  4751.2 2322.88  4831.2 2318.92  4871.1 2319.09
  4877.1 2318.31  4964.6 2316.39  4985.7 2317.30  5019.9 2315.86  5020.1 2315.36
  5023.9 2315.86  5043.0 2317.41  5058.1 2317.15  5076.8 2318.47  5109.4 2319.37
  5151.6 2321.96  5172.7 2321.70  5239.2 2324.00  5245.2 2325.12  5274.6 2325.30
  5369.3 2330.40  5405.6 2333.48  5411.6 2334.77  5456.7 2337.03  5469.0 2339.58
  5484.2 2340.83  5514.5 2345.34  5550.8 2352.06  5556.8 2354.03  5645.1 2365.28
#Mann=5,-1,0
  4410.5    0.07       0  5019.9    0.07       0  5023.9    0.07       0
  5076.8   0.035       0  5274.6    0.16       0
Bank Sta=5019.9,5023.9
Exp/Cntr=0.3,0.1

Type RM Length L Ch R = 1,3689,230,230,230
BEGIN DESCRIPTION:
elmc312
END DESCRIPTION:
XS GIS Cut Line= 3
      1499697.58      6770084.83      1499466.97      6769627.28
      1499049.84      6769147.95
#Sta/Elev= 30
  4433.7 2323.83  4508.5 2325.18  4515.7 2324.49  4604.9 2324.88  4716.4 2323.91
  4789.0 2320.58  4894.9 2317.98  4900.5 2317.02  4917.2 2316.64  4942.9 2313.53
  4980.7 2311.78  4981.0 2311.28  4984.7 2311.78  5109.1 2317.57  5181.2 2320.35
  5209.6 2320.57  5281.0 2324.77  5336.9 2328.08  5379.6 2332.09  5393.8 2332.23
  5435.6 2337.21  5451.9 2338.32  5478.3 2342.32  5485.9 2342.49  5506.8 2346.23
  5535.3 2348.36  5556.2 2352.99  5563.8 2353.52  5570.4 2355.49  5581.5 2356.49
#Mann=6,-1,0
  4433.7    0.07       0  4980.7    0.07       0  4984.7    0.07       0
  5109.1   0.035       0  5281.0    0.16       0  5451.9    0.07       0
Bank Sta=4980.7,4984.7
Exp/Cntr=0.3,0.1

Type RM Length L Ch R = 1,3459,239,239,239
BEGIN DESCRIPTION:
elmc311
END DESCRIPTION:
XS GIS Cut Line= 3
      1499851.29      6770033.56      1499609.72      6769444.28
      1499200.64      6769002.32
#Sta/Elev= 30
  4392.5 2323.25  4485.0 2323.26  4560.6 2321.76  4593.0 2321.91  4709.4 2318.92
  4816.2 2317.02  4821.6 2317.45  4840.2 2316.06  4845.6 2316.51  4869.6 2313.56
  4960.5 2309.96  4998.3 2307.32  4998.6 2306.82  5002.3 2307.32  5005.7 2308.04
  5024.3 2307.96  5086.7 2310.39  5115.1 2313.25  5181.2 2316.54  5331.2 2322.33
  5348.7 2322.49  5355.5 2323.68  5433.2 2327.90  5475.7 2331.09  5483.1 2330.95
  5504.0 2332.79  5511.4 2332.50  5560.7 2336.21  5610.2 2337.55  5631.6 2338.94
#Mann=5,-1,0
  4392.5    0.07       0  4998.3    0.07       0  5002.3    0.07       0
  5181.2   0.035       0  5331.2    0.07       0
Bank Sta=4998.3,5002.3
Exp/Cntr=0.3,0.1

Type RM Length L Ch R = 1,3220,218,218,218
BEGIN DESCRIPTION:
elmc310
END DESCRIPTION:
XS GIS Cut Line= 3
      1499946.45      6769960.35      1499803.71      6769294.21
      1499320.54      6768847.64
#Sta/Elev= 30
  4366.3 2323.24  4445.1 2323.36  4450.5 2322.33  4511.9 2321.82  4522.1 2320.50
  4675.5 2316.77  4716.4 2313.23  4757.3 2311.21  4919.0 2304.72  4924.1 2305.19
  4931.2 2304.11  4980.3 2303.19  4980.6 2302.69  4984.3 2303.19  5012.7 2303.83
  5023.2 2306.20  5047.6 2308.28  5051.0 2309.36  5136.0 2313.92  5164.4 2316.26
  5206.9 2318.28  5248.4 2318.97  5305.6 2319.67  5378.3 2322.26  5419.2 2323.09
  5567.5 2325.99  5589.1 2327.23  5610.1 2326.75  5652.6 2328.16  5705.5 2328.26
#Mann=6,-1,0
  4366.3    0.07       0  4980.3    0.07       0  4984.3    0.07       0
  5248.4   0.035       0  5378.3    0.16       0  5419.2    0.07       0
Bank Sta=4980.3,4984.3
Exp/Cntr=0.3,0.1

Type RM Length L Ch R = 1,3002,137,137,137
BEGIN DESCRIPTION:
elmc309
END DESCRIPTION:
XS GIS Cut Line= 4
      1500096.52      6769780.97      1500067.24      6769414.99
      1499920.84      6769078.26      1499434.00      6768818.37
#Sta/Elev= 30
  4527.3 2323.15  4607.3 2319.85  4735.2 2316.81  4831.2 2309.89  4858.1 2306.57
  4967.9 2301.08  4985.9 2299.72  5000.2 2297.23  5014.8 2297.71  5020.0 2297.01
  5020.3 2296.51  5024.0 2297.01  5032.7 2297.75  5038.2 2299.59  5152.9 2303.89
  5184.3 2306.14  5213.2 2309.38  5267.7 2311.93  5289.6 2314.48  5317.3 2316.01
  5399.4 2315.64  5414.5 2316.38  5472.3 2319.60  5587.8 2322.66  5698.3 2323.72
  5733.0 2323.55  5739.3 2324.33  5761.3 2323.94  5777.6 2324.73  5813.5 2323.87
#Mann=6,-1,0
  4527.3    0.07       0  5020.0    0.07       0  5024.0    0.07       0
  5414.5   0.035       0  5587.8    0.16       0  5698.3    0.07       0
Bank Sta=5020,5024
Exp/Cntr=0.3,0.1

Type RM Length L Ch R = 1,2865,116,116,116
BEGIN DESCRIPTION:
elma821
END DESCRIPTION:
XS GIS Cut Line= 4
      1500135.66      6769749.61      1500121.61      6769272.11
      1500002.24      6769009.96      1499735.39      6768768.86
#Sta/Elev= 30
  4446.2 2322.37  4507.8 2319.47  4627.9 2317.36  4687.9 2312.45  4747.9 2309.03
  4788.0 2304.88  4939.4 2299.16  4961.4 2296.82  4971.5 2296.82  4977.0 2295.34
  4998.0 2293.40  4998.3 2292.90  5002.0 2293.40  5005.3 2295.20  5046.1 2297.21
  5051.6 2299.25  5069.2 2298.72  5074.7 2300.16  5092.2 2300.46  5097.7 2302.00
  5108.0 2302.67  5166.9 2306.55  5172.4 2308.29  5232.9 2310.80  5253.8 2313.08
  5261.3 2315.27  5275.4 2316.05  5374.1 2316.63  5517.5 2319.82  5571.6 2320.17
#Mann=6,-1,0
  4446.2    0.07       0  4998.0    0.07       0  5002.0    0.07       0
  5005.3    0.16       0  5108.0    0.07       0  5517.5   0.035       0
Bank Sta=4998,5002
Exp/Cntr=0.3,0.1

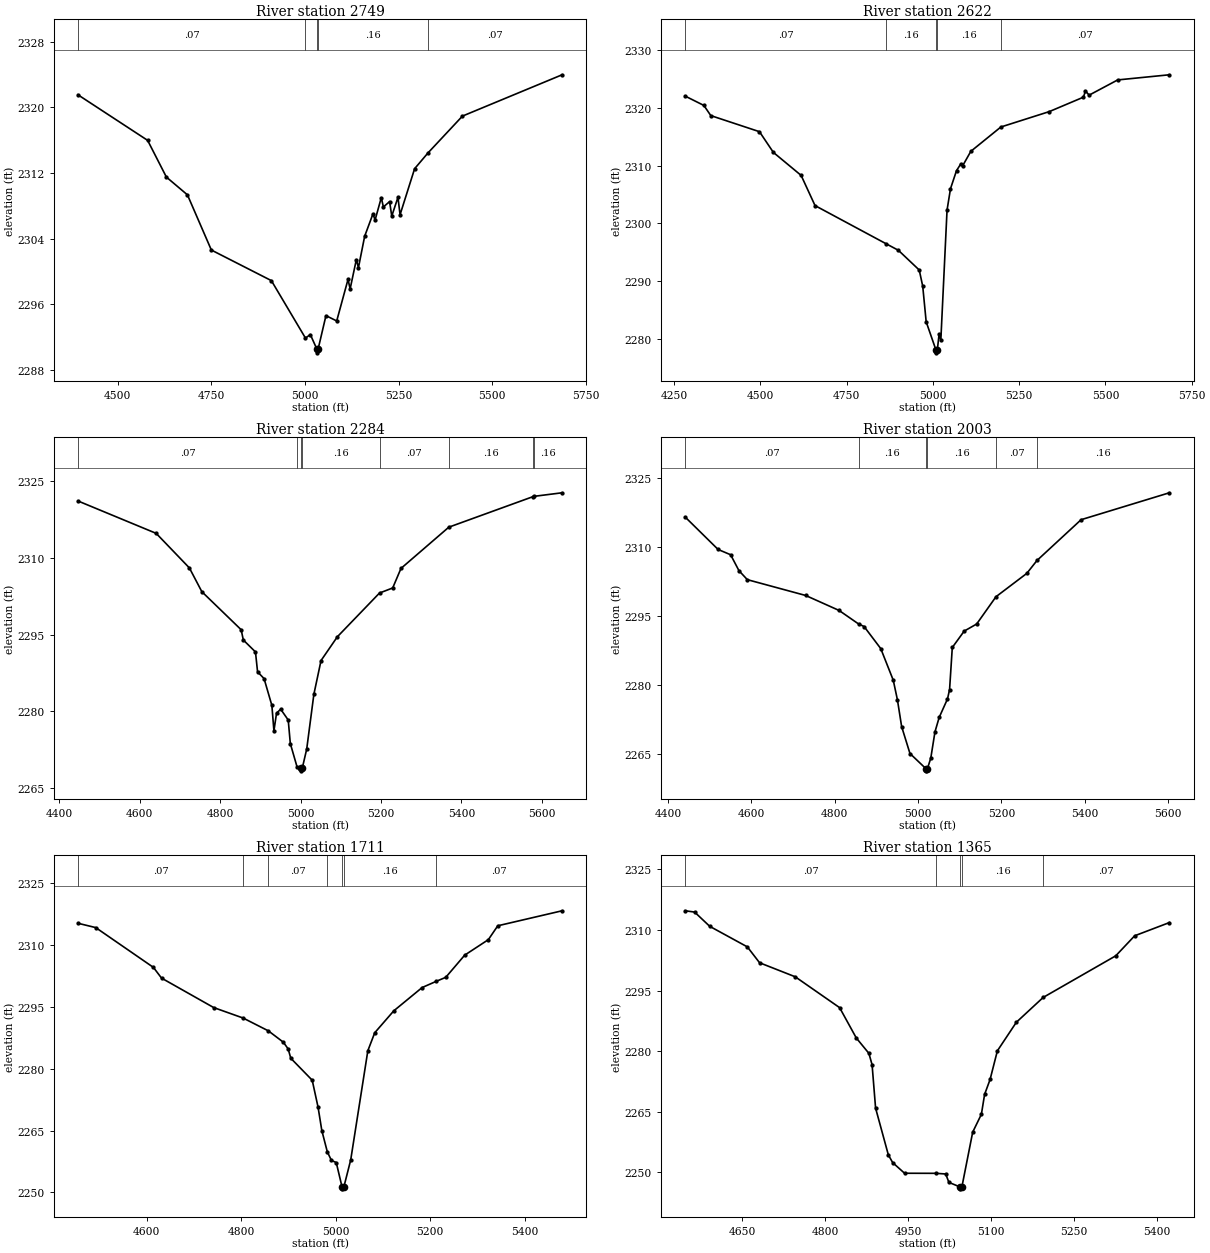
Type RM Length L Ch R = 1,2749,127,127,127
BEGIN DESCRIPTION:
elma820
END DESCRIPTION:
XS GIS Cut Line= 4
      1500168.43      6769723.87      1500189.49      6769190.19
      1500149.70      6769026.35      1499881.37      6768501.35
#Sta/Elev= 30
  4393.9 2321.54  4579.9 2315.98  4630.0 2311.50  4686.2 2309.33  4750.0 2302.60
  4910.2 2298.87  5001.2 2291.86  5014.2 2292.29  5031.2 2290.56  5031.4 2290.06
  5035.2 2290.56  5055.9 2294.60  5084.6 2293.95  5114.8 2299.02  5120.4 2297.86
  5137.0 2301.43  5142.6 2300.45  5159.2 2304.28  5181.4 2307.02  5187.0 2306.26
  5203.6 2308.99  5209.2 2307.86  5225.8 2308.51  5231.5 2306.74  5248.1 2309.03
  5253.7 2306.91  5292.5 2312.52  5328.1 2314.44  5420.2 2318.94  5686.2 2323.98
#Mann=5,-1,0
  4393.9    0.07       0  5001.2    0.16       0  5031.2    0.07       0
  5035.2    0.16       0  5328.1    0.07       0
Bank Sta=5031.2,5035.2
Exp/Cntr=0.3,0.1

Type RM Length L Ch R = 1,2622,338,338,338
BEGIN DESCRIPTION:
elmc308
END DESCRIPTION:
XS GIS Cut Line= 3
      1500184.37      6769751.73      1500275.87      6768968.45
      1500030.64      6768404.79
#Sta/Elev= 30
  4282.1 2322.02  4336.2 2320.41  4356.3 2318.65  4497.3 2315.87  4537.6 2312.29
  4618.1 2308.31  4658.4 2303.09  4863.5 2296.52  4900.0 2295.36  4960.4 2291.95
  4970.5 2289.16  4980.5 2283.00  5008.8 2278.13  5009.0 2277.63  5012.8 2278.13
  5017.9 2280.81  5023.0 2279.85  5041.0 2302.31  5051.0 2306.01  5068.4 2309.13
  5081.0 2310.31  5086.5 2310.00  5109.9 2312.47  5197.0 2316.68  5337.2 2319.34
  5436.4 2321.84  5442.0 2322.91  5452.9 2322.19  5535.6 2324.82  5685.4 2325.71
#Mann=5,-1,0
  4282.1    0.07       0  4863.5    0.16       0  5008.8    0.07       0
  5012.8    0.16       0  5197.0    0.07       0
Bank Sta=5008.8,5012.8
Exp/Cntr=0.3,0.1

Type RM Length L Ch R = 1,2284,281,281,281
BEGIN DESCRIPTION:
elmc307
END DESCRIPTION:
XS GIS Cut Line= 3
      1500349.09      6769806.59      1500524.76      6769122.18
      1500645.55      6768639.05
#Sta/Elev= 30
  4446.0 2321.15  4640.7 2314.81  4723.3 2308.05  4754.3 2303.40  4852.1 2295.96
  4857.5 2293.95  4887.7 2291.62  4892.9 2287.73  4909.1 2286.40  4928.5 2281.16
  4933.6 2276.19  4940.1 2279.63  4950.4 2280.42  4969.2 2278.30  4974.4 2273.70
  4990.9 2269.20  5000.1 2268.86  5000.3 2268.36  5004.1 2268.86  5015.2 2272.63
  5033.0 2283.33  5050.8 2289.93  5091.5 2294.59  5196.3 2303.14  5229.1 2304.13
  5249.7 2307.95  5368.7 2316.02  5578.4 2322.00  5580.4 2322.05  5650.6 2322.75
#Mann=8,-1,0
  4446.0    0.07       0  4990.9    0.16       0  5000.1    0.07       0
  5004.1    0.16       0  5196.3    0.07       0  5368.7    0.16       0
  5578.4    0.07       0  5580.4    0.16       0
Bank Sta=5000.1,5004.1
Exp/Cntr=0.3,0.1

Type RM Length L Ch R = 1,2003,292,292,292
BEGIN DESCRIPTION:
elmc306
END DESCRIPTION:
XS GIS Cut Line= 3
      1500700.45      6769846.90      1500733.39      6769136.82
      1500700.46      6768686.66
#Sta/Elev= 30
  4441.2 2316.58  4520.2 2309.52  4550.2 2308.37  4570.2 2304.90  4590.3 2302.94
  4730.4 2299.49  4810.5 2296.23  4857.2 2293.29  4870.6 2292.72  4910.6 2287.91
  4940.6 2281.02  4950.6 2276.75  4960.7 2270.91  4980.7 2265.04  5018.7 2261.76
  5019.0 2261.26  5022.7 2261.76  5030.7 2264.04  5040.7 2269.75  5050.8 2272.90
  5070.8 2276.94  5075.8 2278.99  5082.3 2288.15  5110.8 2291.72  5140.8 2293.27
  5187.2 2299.22  5261.2 2304.31  5285.6 2307.12  5391.5 2316.01  5603.4 2321.88
#Mann=6,-1,0
  4441.2    0.07       0  4857.2    0.16       0  5018.7    0.07       0
  5022.7    0.16       0  5187.2    0.07       0  5285.6    0.16       0
Bank Sta=5018.7,5022.7
Exp/Cntr=0.3,0.1

Type RM Length L Ch R = 1,1711,346,346,346
BEGIN DESCRIPTION:
elmc305
END DESCRIPTION:
XS GIS Cut Line= 3
      1500887.13      6769824.91      1501004.25      6769199.04
      1501011.55      6768812.05
#Sta/Elev= 30
  4455.0 2315.32  4492.6 2314.27  4614.6 2304.61  4631.8 2302.01  4742.1 2294.86
  4804.3 2292.32  4857.8 2289.20  4889.3 2286.46  4899.5 2284.83  4905.1 2282.56
  4950.4 2277.23  4962.8 2270.67  4970.7 2265.02  4982.3 2259.86  4991.1 2257.75
  5001.2 2257.26  5013.4 2251.37  5013.6 2250.87  5017.4 2251.37  5031.8 2257.89
  5068.0 2284.38  5082.6 2288.75  5122.8 2294.06  5182.8 2299.72  5213.1 2301.25
  5232.8 2302.20  5272.8 2307.58  5322.8 2311.34  5342.8 2314.71  5478.8 2318.35
#Mann=7,-1,0
  4455.0    0.07       0  4804.3    0.16       0  4857.8    0.07       0
  4982.3    0.16       0  5013.4    0.07       0  5017.4    0.16       0
  5213.1    0.07       0
Bank Sta=5013.4,5017.4
Exp/Cntr=0.3,0.1

Type RM Length L Ch R = 1,1365,305,305,305
BEGIN DESCRIPTION:
elmc304
END DESCRIPTION:
XS GIS Cut Line= 3
      1501029.85      6769824.97      1501333.66      6769305.19
      1501406.69      6769042.30
#Sta/Elev= 30
  4547.2 2314.75  4564.2 2314.43  4591.5 2310.90  4659.5 2305.81  4681.6 2301.88
  4746.0 2298.41  4826.2 2290.77  4856.4 2283.25  4879.1 2279.46  4884.9 2276.63
  4891.2 2265.90  4914.3 2254.30  4922.1 2252.40  4943.6 2249.77  5000.2 2249.75
  5017.9 2249.59  5023.7 2247.51  5043.2 2246.41  5043.5 2245.91  5047.2 2246.41
  5066.7 2259.95  5082.4 2264.37  5088.2 2269.29  5098.1 2272.98  5111.3 2280.08
  5145.6 2287.15  5194.0 2293.29  5325.2 2303.60  5359.4 2308.56  5422.1 2311.83
#Mann=5,-1,0
  4547.2    0.07       0  5000.2    0.16       0  5043.2    0.07       0
  5047.2    0.16       0  5194.0    0.07       0
Bank Sta=5043.2,5047.2
Exp/Cntr=0.3,0.1

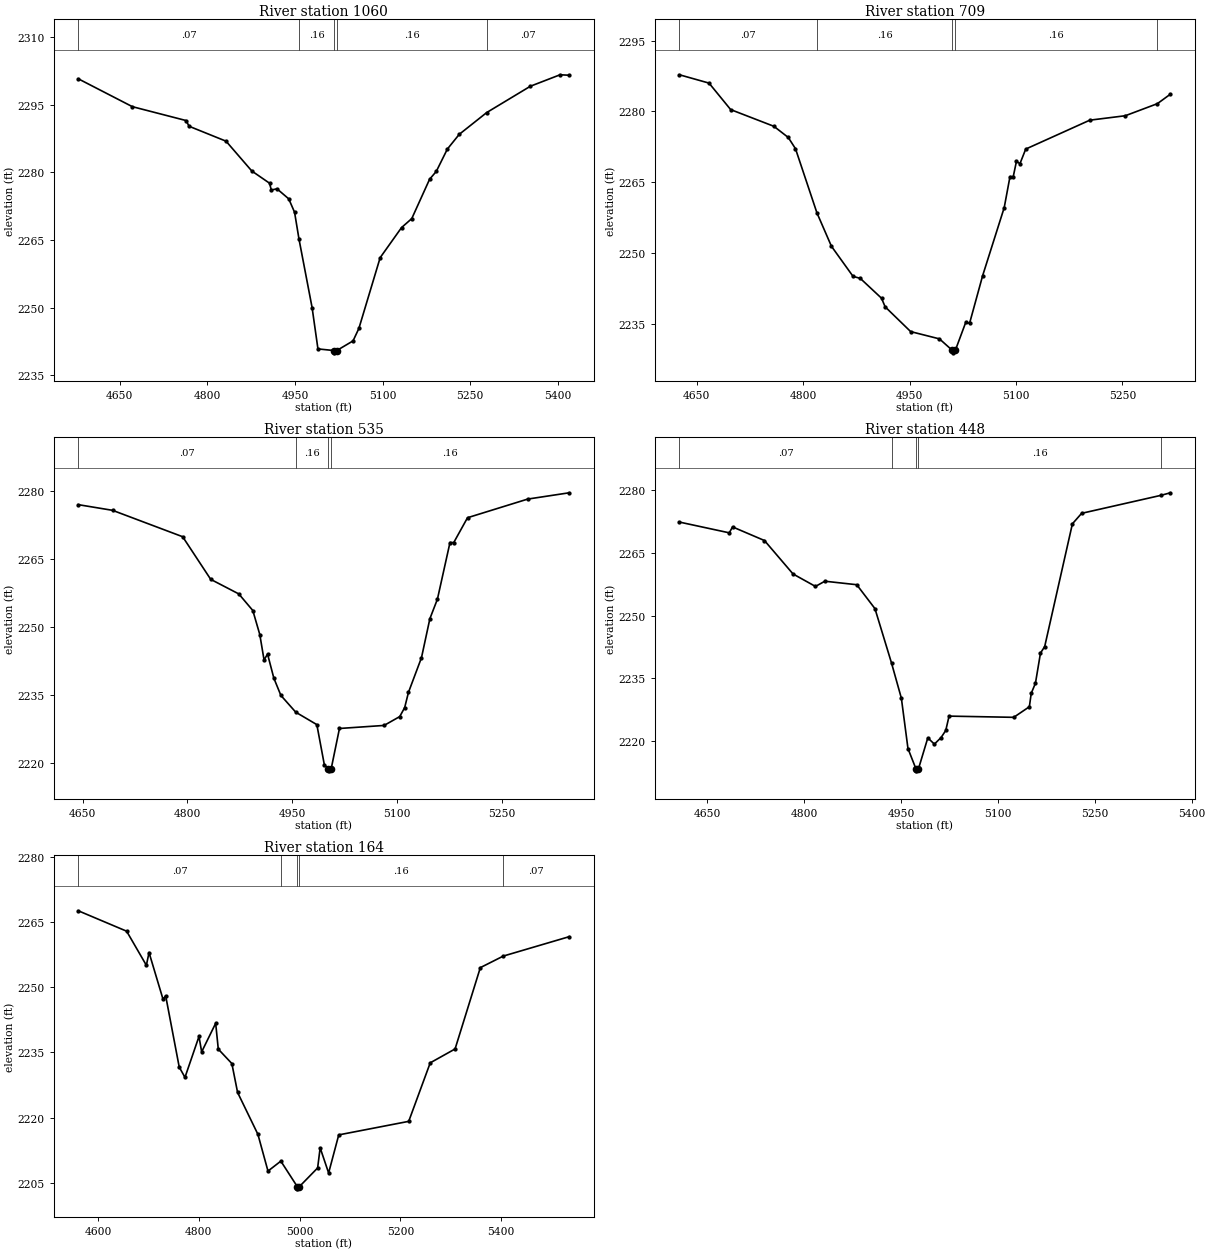
Type RM Length L Ch R = 1,1060,351,351,351
BEGIN DESCRIPTION:
elmc303
END DESCRIPTION:
XS GIS Cut Line= 4
      1501381.23      6769927.45      1501520.33      6769627.28
      1501531.31      6769414.99      1501480.13      6769122.54
#Sta/Elev= 30
  4579.1 2300.75  4671.7 2294.57  4763.4 2291.50  4768.9 2290.22  4832.0 2286.92
  4876.1 2280.31  4906.4 2277.61  4909.5 2276.10  4919.2 2276.36  4939.3 2274.14
  4949.3 2271.16  4956.9 2265.19  4979.3 2250.03  4989.3 2240.87  5017.4 2240.50
  5017.6 2240.00  5021.4 2240.50  5049.4 2242.65  5059.4 2245.42  5095.8 2261.10
  5132.4 2267.77  5149.9 2269.76  5180.4 2278.48  5191.9 2280.23  5210.8 2285.17
  5231.1 2288.43  5278.2 2293.27  5352.9 2299.10  5403.7 2301.64  5419.4 2301.54
#Mann=5,-1,0
  4579.1    0.07       0  4956.9    0.16       0  5017.4    0.07       0
  5021.4    0.16       0  5278.2    0.07       0
Bank Sta=5017.4,5021.4
Exp/Cntr=0.3,0.1

Type RM Length L Ch R = 1,709,174,174,174
BEGIN DESCRIPTION:
elmc302
END DESCRIPTION:
XS GIS Cut Line= 3
      1501780.20      6769909.12      1501860.73      6769447.94
      1501842.43      6769224.65
#Sta/Elev= 30
  4625.5 2287.76  4667.2 2286.00  4697.7 2280.40  4758.6 2276.87  4778.9 2274.51
  4789.1 2272.13  4819.3 2258.58  4839.8 2251.50  4870.3 2245.13  4880.4 2244.72
  4910.4 2240.52  4915.5 2238.70  4951.5 2233.46  4992.1 2231.92  5010.4 2229.47
  5010.6 2228.97  5014.4 2229.47  5029.4 2235.52  5034.5 2235.19  5053.0 2245.30
  5083.4 2259.68  5091.5 2266.21  5096.1 2266.21  5100.6 2269.43  5105.6 2268.97
  5113.7 2272.05  5204.0 2278.16  5254.1 2279.10  5299.3 2281.65  5317.7 2283.66
#Mann=5,-1,0
  4625.5    0.07       0  4819.3    0.16       0  5010.4    0.07       0
  5014.4    0.16       0  5299.3    0.07       0
Bank Sta=5010.4,5014.4
Exp/Cntr=0.3,0.1

Type RM Length L Ch R = 1,535,87,87,87
BEGIN DESCRIPTION:
elma822
END DESCRIPTION:
XS GIS Cut Line= 4
      1501984.76      6769936.87      1502015.19      6769616.19
      1501935.61      6769419.57      1501872.45      6769262.85
#Sta/Elev= 30
  4643.7 2276.97  4692.8 2275.72  4793.2 2269.90  4833.4 2260.50  4873.6 2257.29
  4893.7 2253.63  4903.7 2248.33  4909.8 2242.72  4914.8 2244.03  4923.8 2238.72
  4933.9 2234.91  4955.2 2231.21  4985.4 2228.47  4996.2 2219.57  5002.0 2218.78
  5002.2 2218.28  5006.0 2218.78  5017.8 2227.62  5081.7 2228.29  5104.1 2230.24
  5111.2 2232.22  5116.6 2235.57  5135.3 2243.24  5147.3 2251.83  5158.1 2256.13
  5176.1 2268.62  5181.5 2268.62  5201.2 2274.09  5287.4 2278.20  5346.9 2279.59
#Mann=4,-1,0
  4643.7    0.07       0  4955.2    0.16       0  5002.0    0.07       0
  5006.0    0.16       0
Bank Sta=5002,5006
Exp/Cntr=0.3,0.1

Type RM Length L Ch R = 1,448,284,284,284
BEGIN DESCRIPTION:
elmc301
END DESCRIPTION:
XS GIS Cut Line= 3
      1502157.21      6769923.80      1502043.74      6769396.69
      1501901.00      6769228.34
#Sta/Elev= 30
  4607.1 2272.42  4684.2 2269.84  4689.3 2271.26  4738.7 2267.99  4782.9 2259.97
  4817.6 2256.98  4832.2 2258.23  4881.5 2257.39  4909.7 2251.65  4935.4 2238.57
  4950.6 2230.15  4960.8 2218.08  4973.1 2213.23  4973.3 2212.73  4977.1 2213.23
  4991.5 2220.64  5001.7 2219.14  5012.0 2220.71  5019.3 2222.42  5024.4 2225.86
  5124.5 2225.57  5148.7 2228.11  5151.6 2231.34  5158.1 2233.75  5165.9 2240.99
  5172.4 2242.54  5215.3 2272.00  5229.6 2274.52  5352.5 2278.84  5367.0 2279.45
#Mann=5,-1,0
  4607.1    0.07       0  4935.4    0.16       0  4973.1    0.07       0
  4977.1    0.16       0  5352.5    0.07       0
Bank Sta=4973.1,4977.1
Exp/Cntr=0.3,0.1

Type RM Length L Ch R = 1,164,0,0,0
BEGIN DESCRIPTION:
elmc300
END DESCRIPTION:
XS GIS Cut Line= 4
      1502230.40      6769879.86      1502329.23      6769550.42
      1502314.59      6769338.13      1502003.46      6769059.94
#Sta/Elev= 30
  4561.0 2267.55  4656.9 2262.86  4696.1 2255.02  4701.4 2257.95  4729.2 2247.19
  4734.4 2248.01  4761.3 2231.62  4772.7 2229.26  4800.5 2238.66  4805.8 2235.12
  4833.6 2241.69  4838.8 2235.75  4865.7 2232.44  4877.1 2225.79  4917.4 2216.17
  4937.4 2207.72  4962.9 2210.01  4995.6 2204.14  4995.8 2203.64  4999.6 2204.14
  5035.9 2208.44  5040.9 2213.07  5057.7 2207.29  5077.8 2216.04  5216.6 2219.15
  5259.3 2232.60  5308.6 2235.79  5358.7 2254.48  5404.3 2257.14  5535.1 2261.60
#Mann=5,-1,0
  4561.0    0.07       0  4962.9    0.16       0  4995.6    0.07       0
  4999.6    0.16       0  5404.3    0.07       0
Bank Sta=4995.6,4999.6
Exp/Cntr=0.3,0.1

Chan Stop Cuts=-1