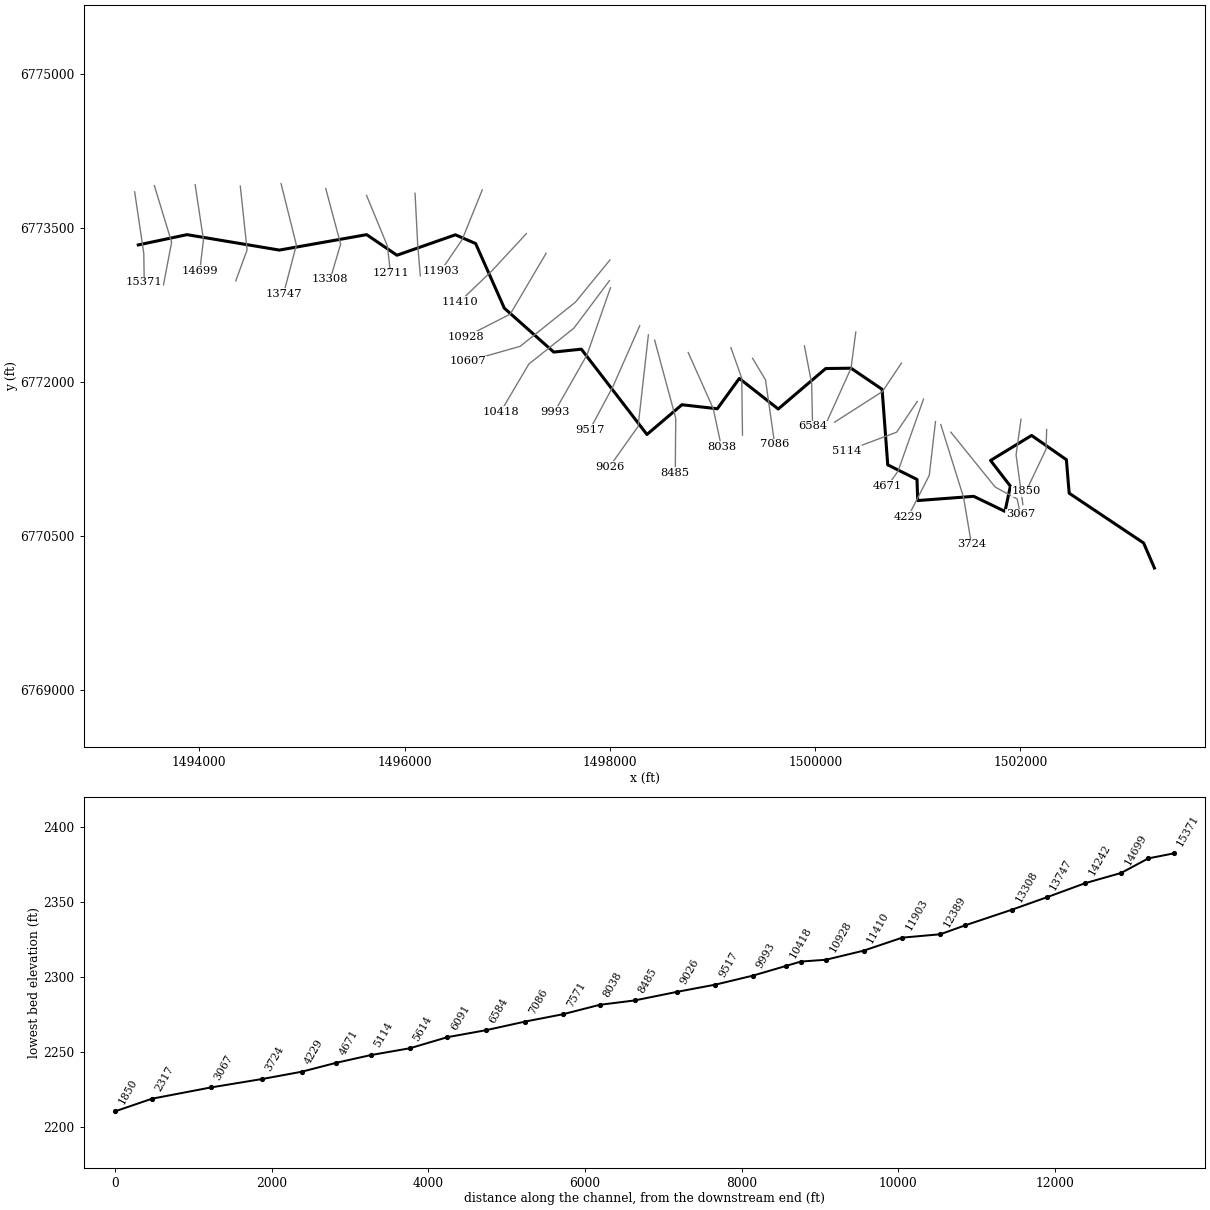
--- Elm 38.prj (project) ---

Proj Title=Elm 38 Base Level Engineering
Current Plan=p01
Default Exp/Contr=0.3,0.1
English Units
Geom File=g01
Flow File=f01
Plan File=p01
BEGIN DESCRIPTION:
Elm 38
END DESCRIPTION:

--- Elm 38.p01 (plan) ---

Plan Title=Multiple Run
Short Identifier=Multiple
Geom File=g01
Flow File=f01
Subcritical Flow
K Sum by GR= 0
Std Step Tol= 0.01
Critical Tol= 0.01
Num of Std Step Trials= 20
Max Error Tol= 0.3
Flow Tol Ratio= 0.001
Split Flow NTrial= 30
Split Flow Tol= 0.02
Split Flow Ratio= 0.02
Log Output Level= 0
Friction Slope Method= 1
Unsteady Friction Slope Method= 2
Unsteady Bridges Friction Slope Method= 1
Parabolic Critical Depth
Global Vel Dist=  1 , 1 , 1
Global Log Level= 0
CheckData=True
Encroach Param= -1, 0, 0, 0
BEGIN DESCRIPTION:
Multiple Run
END DESCRIPTION:

--- Elm 38.f01 (steady flow) ---

Flow Title=Multiple
Number of Profiles=7
Profile Names=10-year,25-year,50-year,1pct_min,100-year,1pct_plu,500-year
River Rch & RM= Elm 38,Reach-1,15371
     203     280     344     262     420     578     633
River Rch & RM= Elm 38,Reach-1,12711
     385     551     692     539     864    1190    1360
River Rch & RM= Elm 38,Reach-1,6584
     497     720     912     715    1150    1580    1830
Boundary for River Rch & Prof#=Elm 38,Reach-1,1
Up Type=0
Dn Type=3
Dn Slope=0.005
Boundary for River Rch & Prof#=Elm 38,Reach-1,2
Up Type=0
Dn Type=3
Dn Slope=0.005
Boundary for River Rch & Prof#=Elm 38,Reach-1,3
Up Type=0
Dn Type=3
Dn Slope=0.005
Boundary for River Rch & Prof#=Elm 38,Reach-1,4
Up Type=0
Dn Type=3
Dn Slope=0.005
Boundary for River Rch & Prof#=Elm 38,Reach-1,5
Up Type=0
Dn Type=3
Dn Slope=0.005
Boundary for River Rch & Prof#=Elm 38,Reach-1,6
Up Type=0
Dn Type=3
Dn Slope=0.005
Boundary for River Rch & Prof#=Elm 38,Reach-1,7
Up Type=0
Dn Type=3
Dn Slope=0.005

--- Elm 38.g01 (geometry) ---

Geom Title=Existing Conditions

River Reach=Elm 38,Reach-1
Reach XY= 30
      1493405.00      6773338.00      1493880.07      6773438.23
      1494780.08      6773287.80      1495630.12      6773438.30
      1495925.21      6773237.49      1496494.50      6773436.78
      1496691.80      6773351.73      1496971.64      6772721.32
      1497452.55      6772293.46      1497721.71      6772321.71
      1498360.86      6771490.04      1498701.65      6771779.97
      1499046.51      6771740.66      1499260.84      6772036.47
      1499639.84      6771738.38      1500102.46      6772132.99
      1500349.29      6772136.11      1500651.93      6771930.43
      1500706.89      6771193.71      1500992.05      6771051.63
      1500998.43      6770845.69      1501544.47      6770886.92
      1501849.35      6770739.96      1501901.47      6770986.55
      1501708.45      6771236.51      1502108.15      6771480.49
      1502447.20      6771244.21      1502474.40      6770917.34
      1503199.42      6770432.42      1503305.00      6770188.00

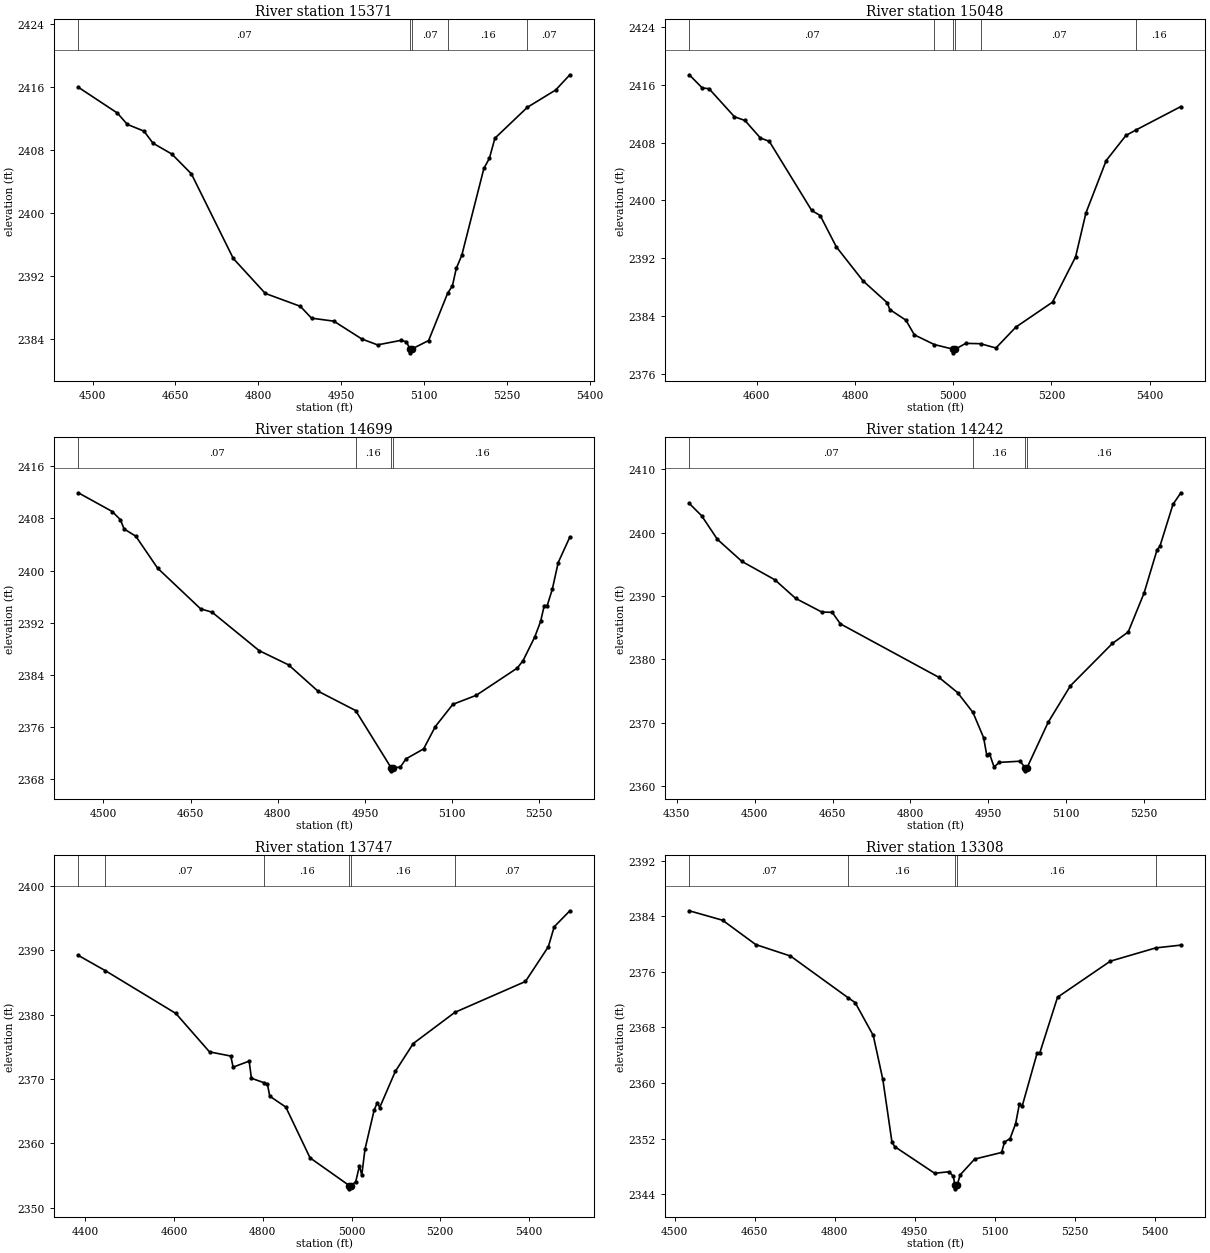
Type RM Length L Ch R = 1,15371,323,323,323
BEGIN DESCRIPTION:
elmc318
END DESCRIPTION:
XS GIS Cut Line= 3
      1493369.98      6773855.61      1493458.85      6773256.88
      1493463.51      6772972.30
#Sta/Elev= 30
  4474.1 2415.97  4544.9 2412.69  4562.7 2411.26  4593.0 2410.40  4609.3 2408.87
  4643.5 2407.49  4678.8 2404.98  4754.7 2394.24  4812.6 2389.81  4876.1 2388.17
  4896.3 2386.67  4936.7 2386.29  4987.3 2384.03  5015.8 2383.28  5058.0 2383.85
  5068.1 2383.68  5074.3 2382.77  5074.5 2382.27  5078.3 2382.77  5108.3 2383.83
  5142.7 2389.83  5151.4 2390.77  5158.3 2392.98  5168.3 2394.64  5208.3 2405.66
  5218.3 2406.95  5228.3 2409.50  5287.0 2413.42  5338.3 2415.62  5364.0 2417.55
#Mann=5,-1,0
  4474.1    0.07       0  5074.3    0.07       0  5078.3    0.07       0
  5142.7    0.16       0  5287.0    0.07       0
Bank Sta=5074.3,5078.3
Exp/Cntr=0.3,0.1

Type RM Length L Ch R = 1,15048,349,349,349
BEGIN DESCRIPTION:
elmc113
END DESCRIPTION:
XS GIS Cut Line= 3
      1493561.74      6773916.45      1493730.14      6773364.46
      1493650.63      6772948.20
#Sta/Elev= 30
  4462.6 2417.36  4489.0 2415.54  4502.8 2415.44  4554.6 2411.56  4576.0 2411.05
  4607.4 2408.63  4625.5 2408.17  4711.9 2398.62  4729.2 2397.92  4762.0 2393.60
  4816.5 2388.89  4865.7 2385.88  4870.9 2384.94  4903.7 2383.47  4921.0 2381.44
  4961.7 2380.10  5000.2 2379.46  5000.4 2378.96  5004.2 2379.46  5025.6 2380.27
  5055.6 2380.22  5087.0 2379.63  5127.7 2382.52  5202.2 2385.96  5249.2 2392.21
  5270.3 2398.29  5311.5 2405.51  5351.7 2408.98  5373.1 2409.77  5463.5 2412.97
#Mann=6,-1,0
  4462.6    0.07       0  4961.7    0.16       0  5000.2    0.07       0
  5004.2    0.16       0  5055.6    0.07       0  5373.1    0.16       0
Bank Sta=5000.2,5004.2
Exp/Cntr=0.3,0.1

Type RM Length L Ch R = 1,14699,457,457,457
BEGIN DESCRIPTION:
elmc112
END DESCRIPTION:
XS GIS Cut Line= 3
      1493959.34      6773925.78      1494040.26      6773388.64
      1494005.00      6773088.00
#Sta/Elev= 30
  4456.8 2411.95  4515.2 2409.07  4529.4 2407.79  4535.5 2406.39  4555.7 2405.28
  4593.3 2400.36  4667.3 2394.11  4687.1 2393.59  4768.1 2387.68  4818.6 2385.50
  4869.2 2381.46  4934.0 2378.48  4994.9 2369.71  4995.2 2369.21  4998.9 2369.71
  5010.7 2369.76  5020.8 2371.06  5051.0 2372.58  5071.1 2376.01  5101.3 2379.43
  5141.6 2380.82  5212.1 2385.00  5222.2 2386.16  5242.3 2389.79  5252.4 2392.19
  5258.6 2394.62  5263.6 2394.58  5272.5 2397.13  5282.6 2401.22  5302.7 2405.15
#Mann=4,-1,0
  4456.8    0.07       0  4934.0    0.16       0  4994.9    0.07       0
  4998.9    0.16       0
Bank Sta=4994.9,4998.9
Exp/Cntr=0.3,0.1

Type RM Length L Ch R = 1,14242,495,495,495
BEGIN DESCRIPTION:
elmc111
END DESCRIPTION:
XS GIS Cut Line= 3
      1494399.02      6773911.78      1494465.50      6773289.22
      1494355.02      6772988.05
#Sta/Elev= 30
  4373.9 2404.59  4397.8 2402.64  4428.0 2398.93  4475.3 2395.45  4538.6 2392.56
  4578.8 2389.62  4629.1 2387.47  4649.2 2387.42  4665.0 2385.60  4854.7 2377.17
  4890.6 2374.78  4920.4 2371.63  4940.9 2367.66  4947.0 2364.86  4952.1 2365.16
  4961.0 2363.05  4971.1 2363.76  5011.3 2363.95  5020.6 2362.93  5020.9 2362.43
  5024.6 2362.93  5065.2 2370.08  5108.1 2375.84  5188.9 2382.51  5219.4 2384.32
  5249.9 2390.44  5275.1 2397.30  5280.4 2397.81  5305.6 2404.43  5320.8 2406.27
#Mann=4,-1,0
  4373.9    0.07       0  4920.4    0.16       0  5020.6    0.07       0
  5024.6    0.16       0
Bank Sta=5020.6,5024.6
Exp/Cntr=0.3,0.1

Type RM Length L Ch R = 1,13747,439,439,439
BEGIN DESCRIPTION:
elmc110
END DESCRIPTION:
XS GIS Cut Line= 3
      1494796.62      6773935.10      1494945.33      6773337.21
      1494820.48      6772861.11
#Sta/Elev= 30
  4383.9 2389.18  4444.8 2386.81  4603.8 2380.17  4679.7 2374.20  4727.7 2373.55
  4732.9 2371.83  4769.1 2372.76  4774.2 2370.10  4802.2 2369.42  4810.4 2369.16
  4815.5 2367.32  4851.7 2365.63  4906.4 2357.74  4995.0 2353.43  4995.3 2352.93
  4999.0 2353.43  5009.5 2354.05  5017.8 2356.52  5023.0 2355.04  5030.2 2359.06
  5050.9 2365.15  5058.2 2366.33  5063.4 2365.55  5098.6 2371.16  5139.0 2375.49
  5233.0 2380.34  5392.0 2385.13  5443.7 2390.53  5456.9 2393.63  5492.2 2396.11
#Mann=6,-1,0
  4383.9   0.035       0  4444.8    0.07       0  4802.2    0.16       0
  4995.0    0.07       0  4999.0    0.16       0  5233.0    0.07       0
Bank Sta=4995,4999
Exp/Cntr=0.3,0.1

Type RM Length L Ch R = 1,13308,597,597,597
BEGIN DESCRIPTION:
elmc109
END DESCRIPTION:
XS GIS Cut Line= 3
      1495231.64      6773888.30      1495376.63      6773345.75
      1495274.23      6773001.33
#Sta/Elev= 30
  4527.5 2384.77  4589.9 2383.41  4652.0 2379.91  4717.1 2378.26  4825.1 2372.26
  4838.3 2371.56  4872.2 2366.83  4890.1 2360.51  4907.1 2351.56  4912.2 2350.85
  4987.2 2347.01  5014.3 2347.23  5022.1 2346.57  5025.3 2345.27  5025.5 2344.77
  5029.3 2345.27  5035.0 2346.78  5062.1 2349.05  5112.6 2350.00  5118.0 2351.49
  5128.5 2352.00  5138.9 2354.15  5145.8 2356.92  5151.0 2356.62  5179.0 2364.25
  5184.2 2364.33  5217.4 2372.33  5316.3 2377.52  5401.4 2379.43  5448.4 2379.83
#Mann=5,-1,0
  4527.5    0.07       0  4825.1    0.16       0  5025.3    0.07       0
  5029.3    0.16       0  5401.4    0.07       0
Bank Sta=5025.3,5029.3
Exp/Cntr=0.3,0.1

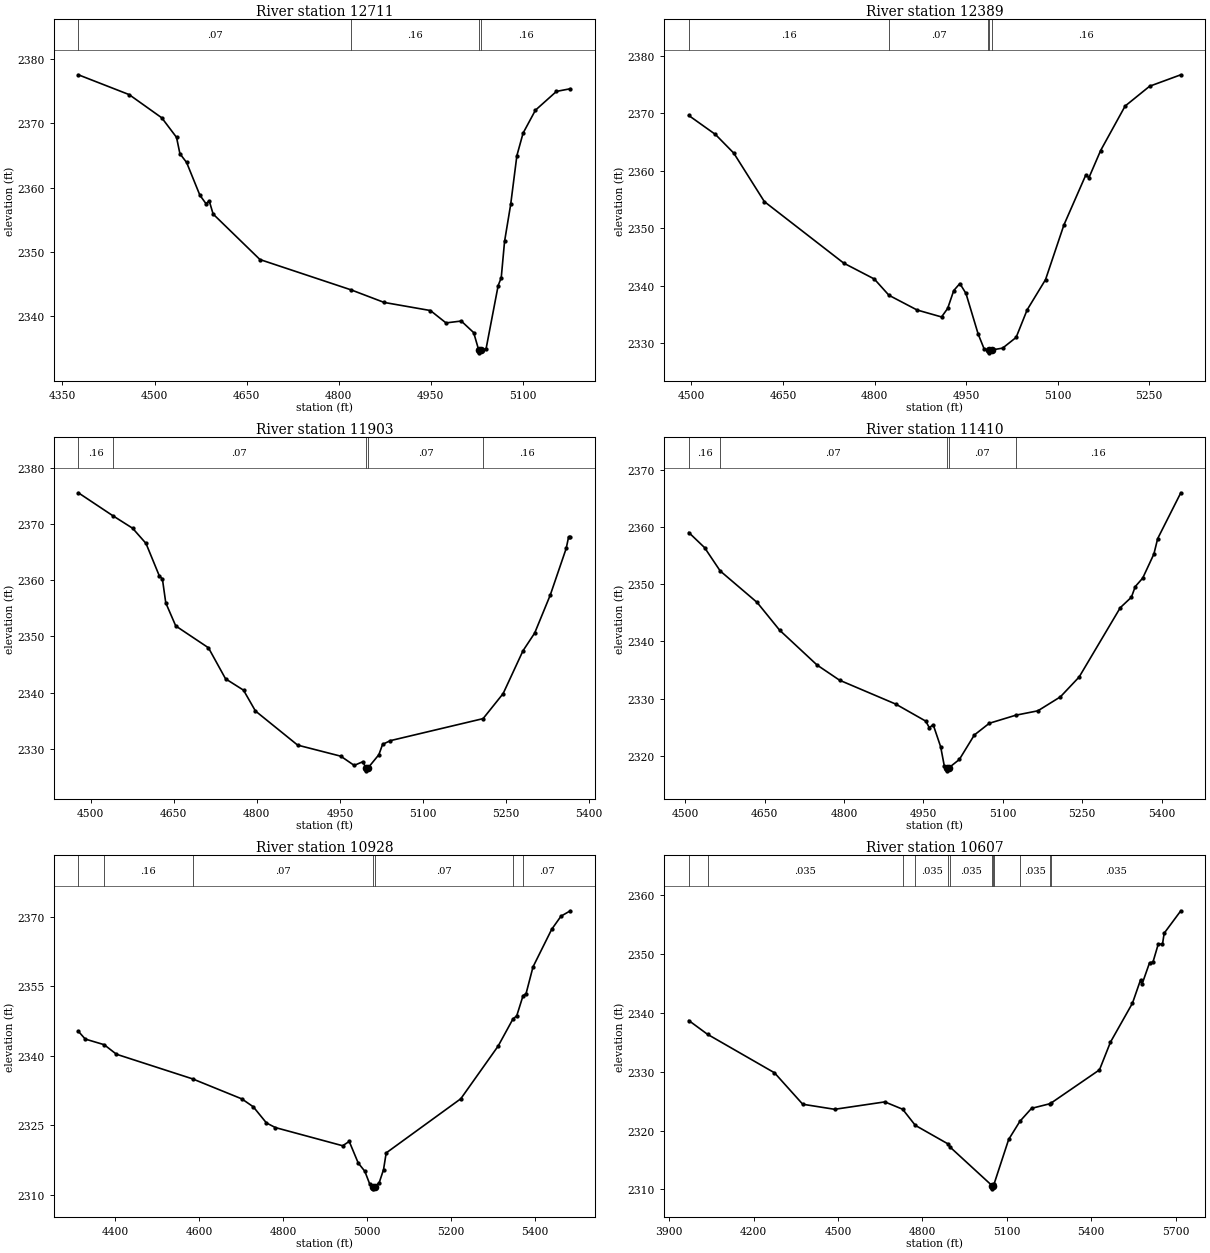
Type RM Length L Ch R = 1,12711,322,322,322
BEGIN DESCRIPTION:
elmc108
END DESCRIPTION:
XS GIS Cut Line= 3
      1495629.09      6773821.05      1495832.76      6773326.92
      1495862.62      6773061.45
#Sta/Elev= 30
  4375.9 2377.52  4458.7 2374.44  4511.9 2370.83  4535.9 2367.80  4541.4 2365.26
  4552.3 2363.90  4573.9 2358.82  4583.8 2357.51  4589.2 2357.92  4595.5 2355.89
  4671.8 2348.82  4820.6 2344.10  4874.1 2342.16  4949.5 2340.90  4974.9 2338.98
  4999.8 2339.27  5020.0 2337.47  5028.0 2334.83  5028.3 2334.33  5032.0 2334.83
  5040.1 2334.91  5059.9 2344.78  5064.9 2346.00  5070.3 2351.63  5080.3 2357.39
  5090.4 2364.97  5100.5 2368.46  5120.6 2372.02  5154.9 2374.94  5177.5 2375.35
#Mann=4,-1,0
  4375.9    0.07       0  4820.6    0.16       0  5028.0    0.07       0
  5032.0    0.16       0
Bank Sta=5028,5032
Exp/Cntr=0.3,0.1

Type RM Length L Ch R = 1,12389,486,486,486
BEGIN DESCRIPTION:
elmc107
END DESCRIPTION:
XS GIS Cut Line= 3
      1496101.64      6773841.61      1496127.55      6773337.88
      1496153.09      6773037.06
#Sta/Elev= 30
  4495.6 2369.58  4539.3 2366.28  4569.3 2363.04  4619.4 2354.61  4749.5 2343.91
  4799.6 2341.15  4823.6 2338.32  4869.7 2335.76  4909.8 2334.55  4919.8 2336.03
  4929.8 2339.14  4939.8 2340.36  4949.8 2338.64  4969.8 2331.58  4979.8 2328.94
  4986.4 2328.83  4987.9 2328.81  4988.1 2328.31  4991.9 2328.81  5009.9 2329.13
  5032.0 2330.99  5050.1 2335.79  5080.2 2341.04  5110.3 2350.54  5146.3 2359.26
  5151.3 2358.76  5170.5 2363.49  5210.6 2371.22  5250.8 2374.67  5301.9 2376.66
#Mann=5,-1,0
  4495.6    0.16       0  4823.6    0.07       0  4986.4    0.16       0
  4987.9    0.07       0  4991.9    0.16       0
Bank Sta=4987.9,4991.9
Exp/Cntr=0.3,0.1

Type RM Length L Ch R = 1,11903,493,493,493
BEGIN DESCRIPTION:
elmc106
END DESCRIPTION:
XS GIS Cut Line= 3
      1496756.51      6773874.36      1496560.98      6773390.36
      1496354.97      6773087.96
#Sta/Elev= 30
  4478.0 2375.58  4540.0 2371.51  4576.0 2369.26  4600.1 2366.56  4624.3 2360.74
  4629.7 2360.25  4635.8 2355.97  4653.8 2351.86  4712.8 2347.97  4743.7 2342.44
  4776.1 2340.42  4797.6 2336.71  4873.8 2330.63  4951.6 2328.66  4975.8 2327.02
  4991.8 2327.69  4996.6 2326.55  4996.8 2326.05  5000.6 2326.55  5020.3 2328.92
  5027.1 2330.77  5041.2 2331.43  5208.4 2335.35  5244.6 2339.81  5280.5 2347.45
  5301.5 2350.59  5329.6 2357.35  5358.4 2365.67  5362.8 2367.74  5365.9 2367.74
#Mann=5,-1,0
  4478.0    0.16       0  4540.0    0.07       0  4996.6    0.07       0
  5000.6    0.07       0  5208.4    0.16       0
Bank Sta=4996.6,5000.6
Exp/Cntr=0.3,0.1

Type RM Length L Ch R = 1,11410,482,482,482
BEGIN DESCRIPTION:
elmc105
END DESCRIPTION:
XS GIS Cut Line= 3
      1497186.81      6773448.65      1496851.48      6773086.72
      1496536.68      6772784.48
#Sta/Elev= 30
  4506.6 2359.06  4536.4 2356.42  4566.0 2352.33  4635.7 2346.83  4678.2 2341.98
  4749.0 2335.88  4791.6 2333.22  4897.6 2329.05  4954.3 2326.07  4961.1 2324.93
  4968.5 2325.43  4982.6 2321.57  4989.4 2318.24  4993.7 2317.87  4994.0 2317.37
  4997.7 2317.87  5017.9 2319.36  5046.2 2323.64  5074.5 2325.69  5124.5 2327.10
  5166.3 2327.87  5208.8 2330.31  5244.3 2333.79  5322.0 2345.91  5343.0 2347.74
  5350.3 2349.60  5364.4 2351.09  5385.5 2355.29  5392.7 2358.00  5436.4 2366.01
#Mann=5,-1,0
  4506.6    0.16       0  4566.0    0.07       0  4993.7    0.07       0
  4997.7    0.07       0  5124.5    0.16       0
Bank Sta=4993.7,4997.7
Exp/Cntr=0.3,0.1

Type RM Length L Ch R = 1,10928,321,321,321
BEGIN DESCRIPTION:
elmc104
END DESCRIPTION:
XS GIS Cut Line= 3
      1497378.61      6773256.91      1497029.53      6772663.81
      1496598.73      6772443.65
#Sta/Elev= 30
  4311.8 2345.30  4328.4 2343.62  4373.3 2342.41  4402.6 2340.35  4584.0 2335.03
  4701.3 2330.71  4728.6 2329.00  4759.9 2325.52  4781.3 2324.52  4941.4 2320.60
  4957.1 2321.53  4978.5 2316.87  4994.2 2315.10  5006.2 2312.26  5014.3 2311.80
  5014.6 2311.30  5018.3 2311.80  5028.5 2312.63  5038.8 2315.45  5045.1 2319.05
  5222.8 2330.74  5311.7 2342.10  5346.9 2347.93  5356.1 2348.65  5371.1 2352.98
  5378.3 2353.43  5394.9 2359.21  5439.4 2367.32  5461.6 2370.15  5483.8 2371.31
#Mann=7,-1,0
  4311.8    0.07       0  4373.3    0.16       0  4584.0    0.07       0
  5014.3    0.07       0  5018.3    0.07       0  5346.9    0.16       0
  5371.1    0.07       0
Bank Sta=5014.3,5018.3
Exp/Cntr=0.3,0.1

Type RM Length L Ch R = 1,10607,189,189,189
BEGIN DESCRIPTION:
elmc317
END DESCRIPTION:
XS GIS Cut Line= 4
      1498000.73      6773191.42      1497663.93      6772779.78
      1497126.01      6772349.45      1496618.09      6772204.99
#Sta/Elev= 30
  3969.5 2338.72  4036.0 2336.38  4274.1 2329.83  4374.5 2324.48  4488.0 2323.62
  4666.2 2324.88  4729.6 2323.63  4774.6 2320.89  4892.0 2317.70  4898.5 2317.18
  5048.4 2310.59  5048.6 2310.09  5052.4 2310.59  5054.3 2310.88  5106.4 2318.49
  5146.4 2321.58  5187.7 2323.78  5254.8 2324.59  5256.2 2324.65  5429.2 2330.33
  5468.2 2335.04  5546.4 2341.67  5575.1 2345.62  5580.3 2344.88  5607.2 2348.55
  5619.3 2348.66  5638.3 2351.75  5653.2 2351.71  5659.1 2353.57  5718.3 2357.39
#Mann=12,-1,0
  3969.5    0.07       0  4036.0   0.035       0  4729.6   0.063       0
  4774.6   0.035       0  4892.0   0.063       0  4898.5   0.035       0
  5048.4   0.035       0  5052.4   0.035       0  5054.3   0.063       0
  5146.4   0.035       0  5254.8   0.063       0  5256.2   0.035       0
Bank Sta=5048.4,5052.4
Exp/Cntr=0.3,0.1

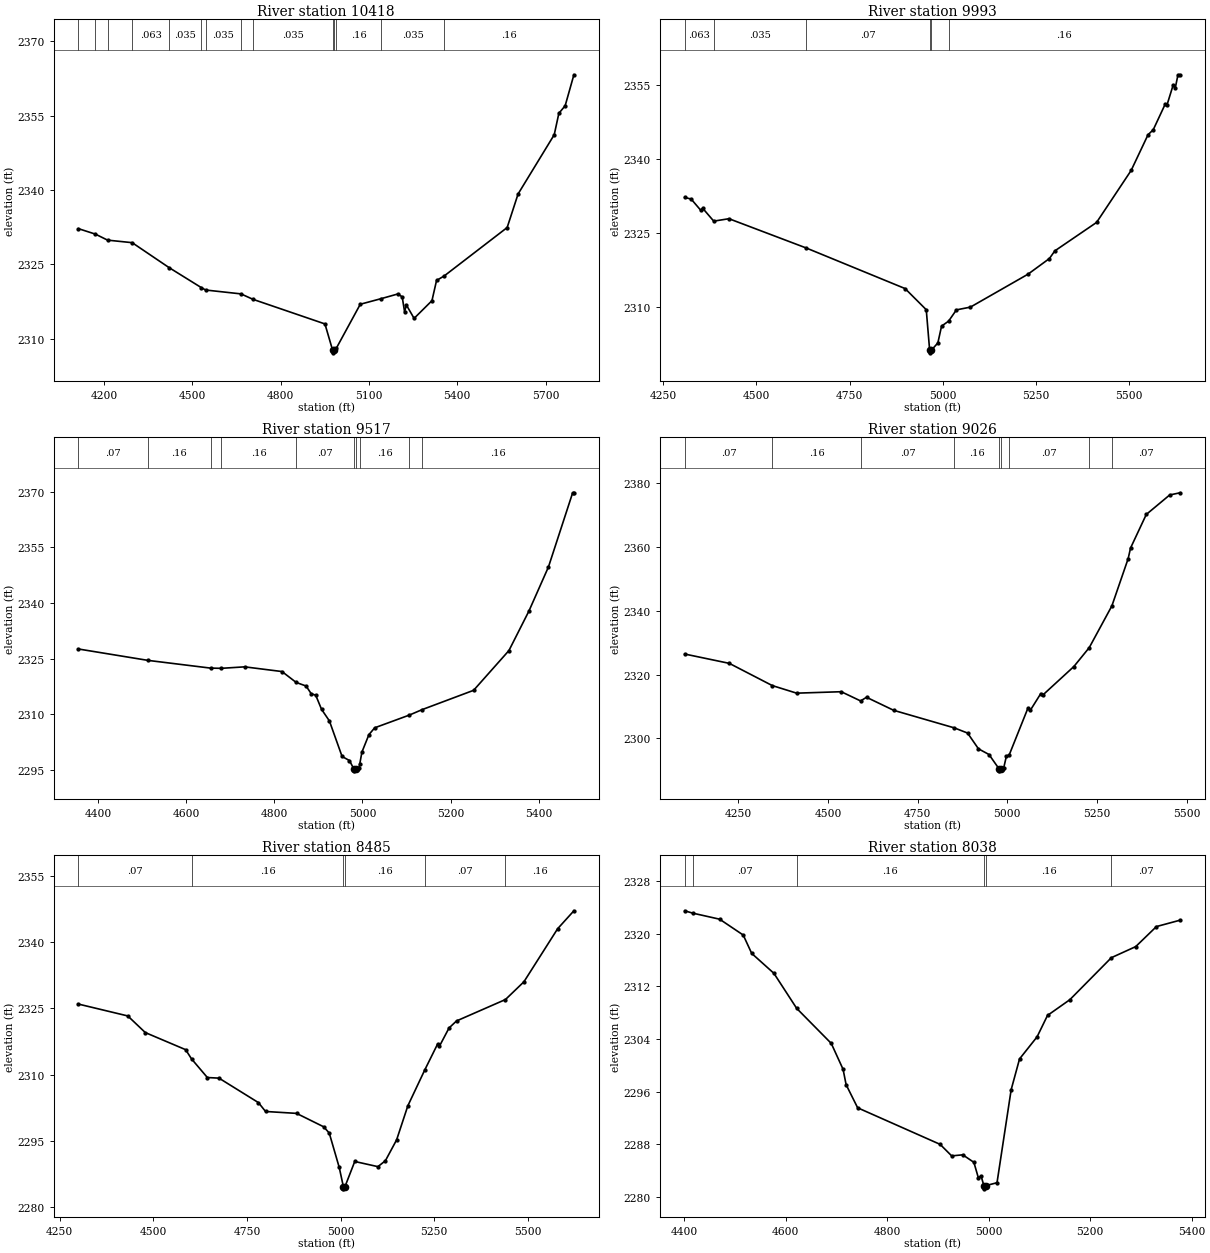
Type RM Length L Ch R = 1,10418,425,425,425
BEGIN DESCRIPTION:
elmc103
END DESCRIPTION:
XS GIS Cut Line= 4
      1497996.00      6772990.23      1497649.89      6772527.19
      1497210.21      6772176.38      1496934.23      6771708.61
#Sta/Elev= 30
  4112.6 2332.21  4170.2 2331.11  4211.4 2329.90  4295.0 2329.39  4419.9 2324.38
  4529.9 2320.33  4544.7 2319.84  4664.8 2319.06  4705.7 2317.96  4950.2 2313.00
  4976.4 2307.67  4976.7 2307.17  4980.4 2307.67  4988.5 2308.06  5070.3 2316.97
  5141.3 2318.10  5198.4 2319.05  5212.8 2318.45  5220.8 2315.47  5227.2 2316.79
  5253.2 2314.12  5313.9 2317.69  5329.5 2321.77  5355.6 2322.68  5569.5 2332.44
  5606.6 2339.21  5729.5 2351.16  5745.2 2355.48  5766.6 2357.00  5796.3 2363.25
#Mann=14,-1,0
  4112.6   0.035       0  4170.2   0.063       0  4211.4   0.035       0
  4295.0   0.063       0  4419.9   0.035       0  4529.9   0.063       0
  4544.7   0.035       0  4664.8    0.07       0  4705.7   0.035       0
  4976.4    0.07       0  4980.4   0.035       0  4988.5    0.16       0
  5141.3   0.035       0  5355.6    0.16       0
Bank Sta=4976.4,4980.4
Exp/Cntr=0.3,0.1

Type RM Length L Ch R = 1,9993,476,476,476
BEGIN DESCRIPTION:
elmc102
END DESCRIPTION:
XS GIS Cut Line= 3
      1498005.40      6772920.13      1497776.92      6772266.62
      1497462.78      6771713.28
#Sta/Elev= 30
  4307.7 2332.17  4325.0 2331.85  4350.7 2329.58  4356.0 2329.98  4385.6 2327.37
  4426.5 2327.86  4633.9 2321.92  4898.8 2313.70  4955.6 2309.41  4964.7 2301.17
  4965.0 2300.67  4968.9 2301.17  4986.7 2302.68  4996.6 2306.08  5015.5 2307.10
  5036.5 2309.38  5074.0 2309.94  5228.4 2316.61  5285.9 2319.79  5300.4 2321.34
  5412.4 2327.11  5505.1 2337.65  5550.4 2344.89  5564.3 2345.89  5596.0 2351.02
  5601.4 2350.96  5617.6 2354.93  5623.4 2354.37  5630.7 2357.04  5636.3 2357.04
#Mann=6,-1,0
  4307.7   0.063       0  4385.6   0.035       0  4633.9    0.07       0
  4964.7    0.07       0  4968.9    0.07       0  5015.5    0.16       0
Bank Sta=4964.7,4968.9
Exp/Cntr=0.3,0.1

Type RM Length L Ch R = 1,9517,491,491,491
BEGIN DESCRIPTION:
elmc101
END DESCRIPTION:
XS GIS Cut Line= 3
      1498290.73      6772550.62      1498031.36      6771961.05
      1497805.00      6771538.00
#Sta/Elev= 30
  4355.9 2327.57  4513.7 2324.50  4655.4 2322.42  4679.9 2322.36  4732.9 2322.76
  4817.6 2321.49  4849.8 2318.55  4872.2 2317.59  4883.9 2315.51  4894.1 2315.11
  4907.3 2311.30  4925.1 2308.18  4953.9 2298.58  4970.6 2297.49  4980.6 2295.21
  4980.9 2294.71  4984.8 2295.21  4992.4 2295.53  4994.0 2296.57  4998.9 2299.77
  5014.8 2304.48  5027.9 2306.32  5106.5 2309.75  5136.1 2311.25  5252.3 2316.43
  5332.4 2327.15  5377.7 2337.79  5422.1 2349.71  5477.0 2369.71  5479.8 2369.71
#Mann=10,-1,0
  4355.9    0.07       0  4513.7    0.16       0  4655.4    0.07       0
  4679.9    0.16       0  4849.8    0.07       0  4980.6    0.07       0
  4984.8    0.07       0  4994.0    0.16       0  5106.5    0.07       0
  5136.1    0.16       0
Bank Sta=4980.6,4984.8
Exp/Cntr=0.3,0.1

Type RM Length L Ch R = 1,9026,541,541,541
BEGIN DESCRIPTION:
elmc100
END DESCRIPTION:
XS GIS Cut Line= 3
      1498374.90      6772461.67      1498274.77      6771567.87
      1497996.02      6771175.38
#Sta/Elev= 30
  4100.6 2326.42  4225.0 2323.50  4344.8 2316.55  4412.6 2314.18  4537.0 2314.63
  4590.9 2311.75  4607.4 2312.89  4683.2 2308.81  4852.4 2303.31  4889.2 2301.69
  4919.4 2296.77  4948.8 2294.99  4977.6 2290.38  4977.9 2289.88  4981.8 2290.38
  4989.8 2290.79  4997.4 2294.51  5005.0 2294.82  5057.5 2309.54  5063.7 2308.77
  5093.2 2314.05  5099.3 2313.64  5185.4 2322.51  5228.2 2328.42  5291.3 2341.47
  5336.7 2356.26  5343.3 2359.56  5387.2 2370.08  5452.4 2376.17  5481.4 2376.86
#Mann=9,-1,0
  4100.6    0.07       0  4344.8    0.16       0  4590.9    0.07       0
  4852.4    0.16       0  4977.6    0.07       0  4981.8    0.16       0
  5005.0    0.07       0  5228.2    0.16       0  5291.3    0.07       0
Bank Sta=4977.6,4981.8
Exp/Cntr=0.3,0.1

Type RM Length L Ch R = 1,8485,447,447,447
BEGIN DESCRIPTION:
elmc99
END DESCRIPTION:
XS GIS Cut Line= 3
      1498435.72      6772410.22      1498641.52      6771647.82
      1498636.85      6771114.63
#Sta/Elev= 30
  4300.0 2325.94  4431.6 2323.26  4478.4 2319.50  4586.1 2315.63  4601.9 2313.54
  4644.1 2309.33  4675.2 2309.19  4780.4 2303.66  4799.5 2301.65  4882.3 2301.22
  4954.8 2298.18  4969.6 2296.77  4996.3 2288.98  5007.3 2284.65  5007.6 2284.15
  5011.6 2284.65  5037.7 2290.34  5099.5 2289.17  5119.5 2290.50  5149.5 2295.23
  5179.5 2302.94  5225.0 2311.10  5259.0 2316.92  5264.0 2316.44  5289.5 2320.54
  5309.5 2322.13  5440.1 2326.97  5489.5 2330.99  5579.5 2342.99  5622.9 2347.05
#Mann=6,-1,0
  4300.0    0.07       0  4601.9    0.16       0  5007.3    0.07       0
  5011.6    0.16       0  5225.0    0.07       0  5440.1    0.16       0
Bank Sta=5007.3,5011.6
Exp/Cntr=0.3,0.1

Type RM Length L Ch R = 1,8038,467,467,467
BEGIN DESCRIPTION:
elmc98
END DESCRIPTION:
XS GIS Cut Line= 3
      1498763.14      6772288.63      1499007.10      6771741.22
      1499085.76      6771372.42
#Sta/Elev= 30
  4400.7 2323.49  4416.6 2323.13  4469.6 2322.21  4516.1 2319.80  4532.8 2317.01
  4576.6 2313.98  4621.5 2308.65  4689.6 2303.33  4712.9 2299.39  4718.9 2297.05
  4741.6 2293.54  4904.2 2287.98  4926.9 2286.23  4948.8 2286.39  4970.7 2285.25
  4979.4 2282.93  4984.8 2283.18  4990.4 2281.72  4990.7 2281.22  4994.8 2281.72
  5016.3 2282.15  5044.2 2296.30  5060.7 2300.97  5095.3 2304.33  5115.8 2307.58
  5159.8 2309.97  5241.7 2316.36  5289.6 2318.04  5330.5 2321.09  5377.1 2322.06
#Mann=6,-1,0
  4400.7    0.16       0  4416.6    0.07       0  4621.5    0.16       0
  4990.4    0.07       0  4994.8    0.16       0  5241.7    0.07       0
Bank Sta=4990.4,4994.8
Exp/Cntr=0.3,0.1

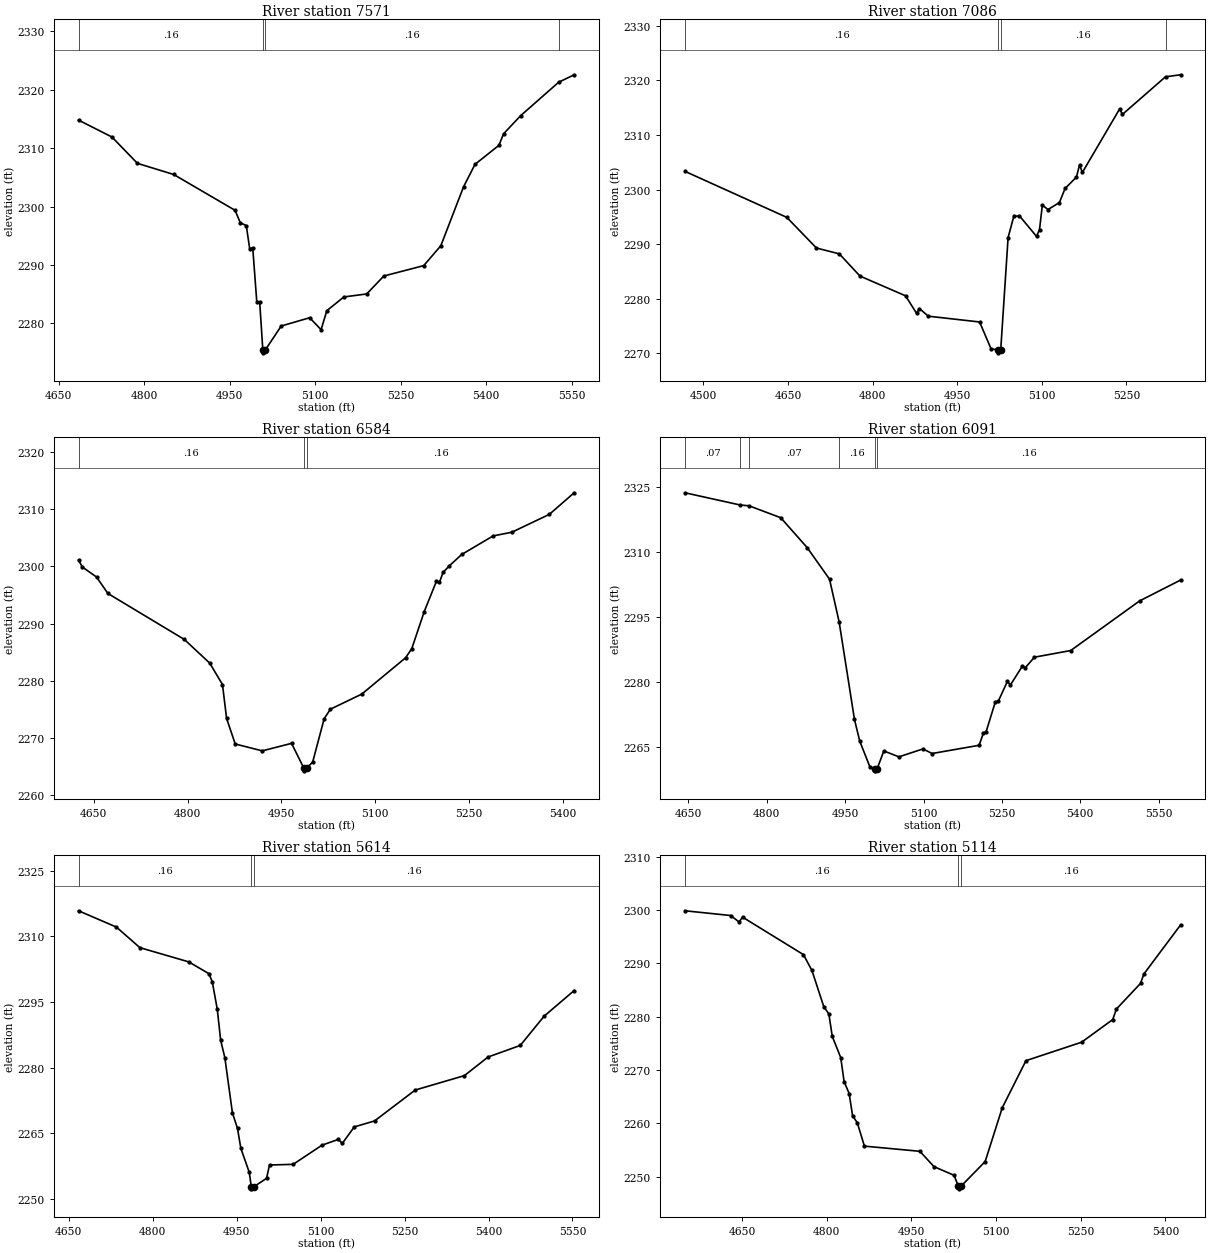
Type RM Length L Ch R = 1,7571,485,485,485
BEGIN DESCRIPTION:
elmc97
END DESCRIPTION:
XS GIS Cut Line= 3
      1499179.44      6772335.40      1499284.73      6772038.41
      1499291.70      6771484.15
#Sta/Elev= 30
  4684.9 2314.81  4743.5 2311.92  4788.2 2307.41  4851.9 2305.50  4959.6 2299.36
  4968.6 2297.25  4979.2 2296.75  4985.2 2292.76  4990.5 2292.96  4997.6 2283.68
  5002.7 2283.68  5008.2 2275.47  5008.5 2274.97  5012.6 2275.47  5040.4 2279.56
  5090.4 2280.98  5110.4 2278.93  5120.4 2282.18  5150.4 2284.54  5190.4 2285.05
  5220.4 2288.12  5290.4 2289.90  5320.4 2293.30  5360.4 2303.42  5380.4 2307.24
  5422.4 2310.50  5430.4 2312.46  5460.4 2315.57  5527.2 2321.30  5554.3 2322.57
#Mann=4,-1,0
  4684.9    0.16       0  5008.2    0.07       0  5012.6    0.16       0
  5527.2    0.07       0
Bank Sta=5008.2,5012.6
Exp/Cntr=0.3,0.1

Type RM Length L Ch R = 1,7086,502,502,502
BEGIN DESCRIPTION:
elmc96
END DESCRIPTION:
XS GIS Cut Line= 3
      1499389.95      6772232.47      1499516.22      6772022.02
      1499605.09      6771395.21
#Sta/Elev= 30
  4467.6 2303.33  4648.1 2294.89  4700.6 2289.27  4741.2 2288.20  4777.7 2284.13
  4858.5 2280.51  4878.0 2277.31  4883.1 2278.18  4898.9 2276.77  4989.8 2275.71
  5010.0 2270.81  5022.8 2270.55  5023.1 2270.05  5027.2 2270.55  5040.3 2291.20
  5050.4 2295.07  5060.5 2295.16  5090.8 2291.39  5096.0 2292.66  5101.0 2297.13
  5111.0 2296.33  5131.2 2297.60  5141.3 2300.19  5161.5 2302.29  5166.9 2304.50
  5172.0 2303.14  5237.9 2314.76  5243.0 2313.78  5319.3 2320.67  5346.1 2321.04
#Mann=4,-1,0
  4467.6    0.16       0  5022.8    0.07       0  5027.2    0.16       0
  5319.3    0.07       0
Bank Sta=5022.8,5027.2
Exp/Cntr=0.3,0.1

Type RM Length L Ch R = 1,6584,493,493,493
BEGIN DESCRIPTION:
elmc95
END DESCRIPTION:
XS GIS Cut Line= 3
      1499895.10      6772354.12      1499965.69      6771986.43
      1499974.61      6771568.33
#Sta/Elev= 30
  4625.6 2301.09  4631.8 2299.87  4654.4 2298.14  4672.6 2295.26  4794.8 2287.23
  4835.5 2283.09  4855.8 2279.36  4862.4 2273.43  4876.2 2268.97  4919.4 2267.77
  4966.3 2269.08  4985.8 2264.78  4986.2 2264.28  4990.6 2264.78  5000.0 2265.80
  5018.4 2273.38  5028.4 2275.05  5078.5 2277.68  5148.5 2284.02  5158.5 2285.62
  5178.5 2292.11  5197.8 2297.36  5202.8 2297.20  5208.5 2298.93  5218.5 2300.08
  5238.5 2302.08  5288.5 2305.31  5318.5 2305.96  5378.5 2309.08  5418.2 2312.85
#Mann=3,-1,0
  4625.6    0.16       0  4985.8    0.07       0  4990.6    0.16       0
Bank Sta=4985.8,4990.6
Exp/Cntr=0.3,0.1

Type RM Length L Ch R = 1,6091,477,477,477
BEGIN DESCRIPTION:
elmc94
END DESCRIPTION:
XS GIS Cut Line= 3
      1500395.59      6772489.79      1500349.29      6772136.11
      1500105.59      6771596.38
#Sta/Elev= 30
  4643.3 2323.62  4748.9 2320.81  4766.0 2320.62  4826.6 2317.88  4877.1 2311.02
  4920.0 2303.74  4938.4 2293.91  4967.8 2271.44  4977.9 2266.44  4997.3 2260.54
  5006.4 2260.12  5006.8 2259.62  5011.3 2260.12  5024.0 2264.20  5052.8 2262.84
  5098.8 2264.66  5116.5 2263.61  5206.4 2265.50  5214.4 2268.22  5219.9 2268.66
  5237.5 2275.51  5243.0 2275.61  5260.7 2280.25  5266.2 2279.36  5289.3 2283.74
  5294.8 2283.36  5312.4 2285.78  5381.8 2287.31  5513.8 2298.74  5592.2 2303.54
#Mann=6,-1,0
  4643.3    0.07       0  4748.9    0.16       0  4766.0    0.07       0
  4938.4    0.16       0  5006.4    0.07       0  5011.3    0.16       0
Bank Sta=5006.4,5011.3
Exp/Cntr=0.3,0.1

Type RM Length L Ch R = 1,5614,500,500,500
BEGIN DESCRIPTION:
elmc93
END DESCRIPTION:
XS GIS Cut Line= 3
      1500839.93      6772185.70      1500655.53      6771908.77
      1500189.89      6771610.47
#Sta/Elev= 30
  4667.3 2315.88  4735.0 2312.15  4777.0 2307.44  4864.2 2304.19  4900.3 2301.49
  4906.3 2299.65  4915.3 2293.33  4921.3 2286.25  4928.8 2282.27  4942.3 2269.65
  4951.4 2266.07  4957.4 2261.51  4972.4 2256.03  4976.0 2252.75  4976.3 2252.25
  4980.9 2252.75  5003.3 2254.65  5008.6 2257.70  5050.9 2257.86  5102.5 2262.25
  5131.3 2263.55  5138.8 2262.66  5160.0 2266.42  5196.3 2267.79  5269.0 2274.86
  5356.9 2278.16  5399.2 2282.42  5456.7 2285.07  5499.4 2291.77  5553.0 2297.63
#Mann=3,-1,0
  4667.3    0.16       0  4976.0    0.07       0  4980.9    0.16       0
Bank Sta=4976,4980.9
Exp/Cntr=0.3,0.1

Type RM Length L Ch R = 1,5114,443,443,443
BEGIN DESCRIPTION:
elmc92
END DESCRIPTION:
XS GIS Cut Line= 3
      1500994.30      6771811.52      1500793.18      6771512.17
      1500308.38      6771330.37
#Sta/Elev= 30
  4548.7 2299.84  4629.7 2298.95  4644.7 2297.73  4650.7 2298.65  4758.7 2291.61
  4773.7 2288.64  4794.7 2281.86  4803.7 2280.48  4809.7 2276.30  4824.7 2272.31
  4830.7 2267.81  4839.7 2265.55  4845.7 2261.40  4854.1 2260.08  4866.7 2255.70
  4965.0 2254.73  4990.0 2251.85  5025.6 2250.23  5033.1 2248.19  5033.5 2247.69
  5038.0 2248.19  5080.7 2252.81  5111.0 2262.90  5153.0 2271.73  5251.6 2275.19
  5306.8 2279.44  5313.2 2281.40  5356.0 2286.22  5362.0 2287.99  5427.1 2297.20
#Mann=3,-1,0
  4548.7    0.16       0  5033.1    0.07       0  5038.0    0.16       0
Bank Sta=5033.1,5038
Exp/Cntr=0.3,0.1

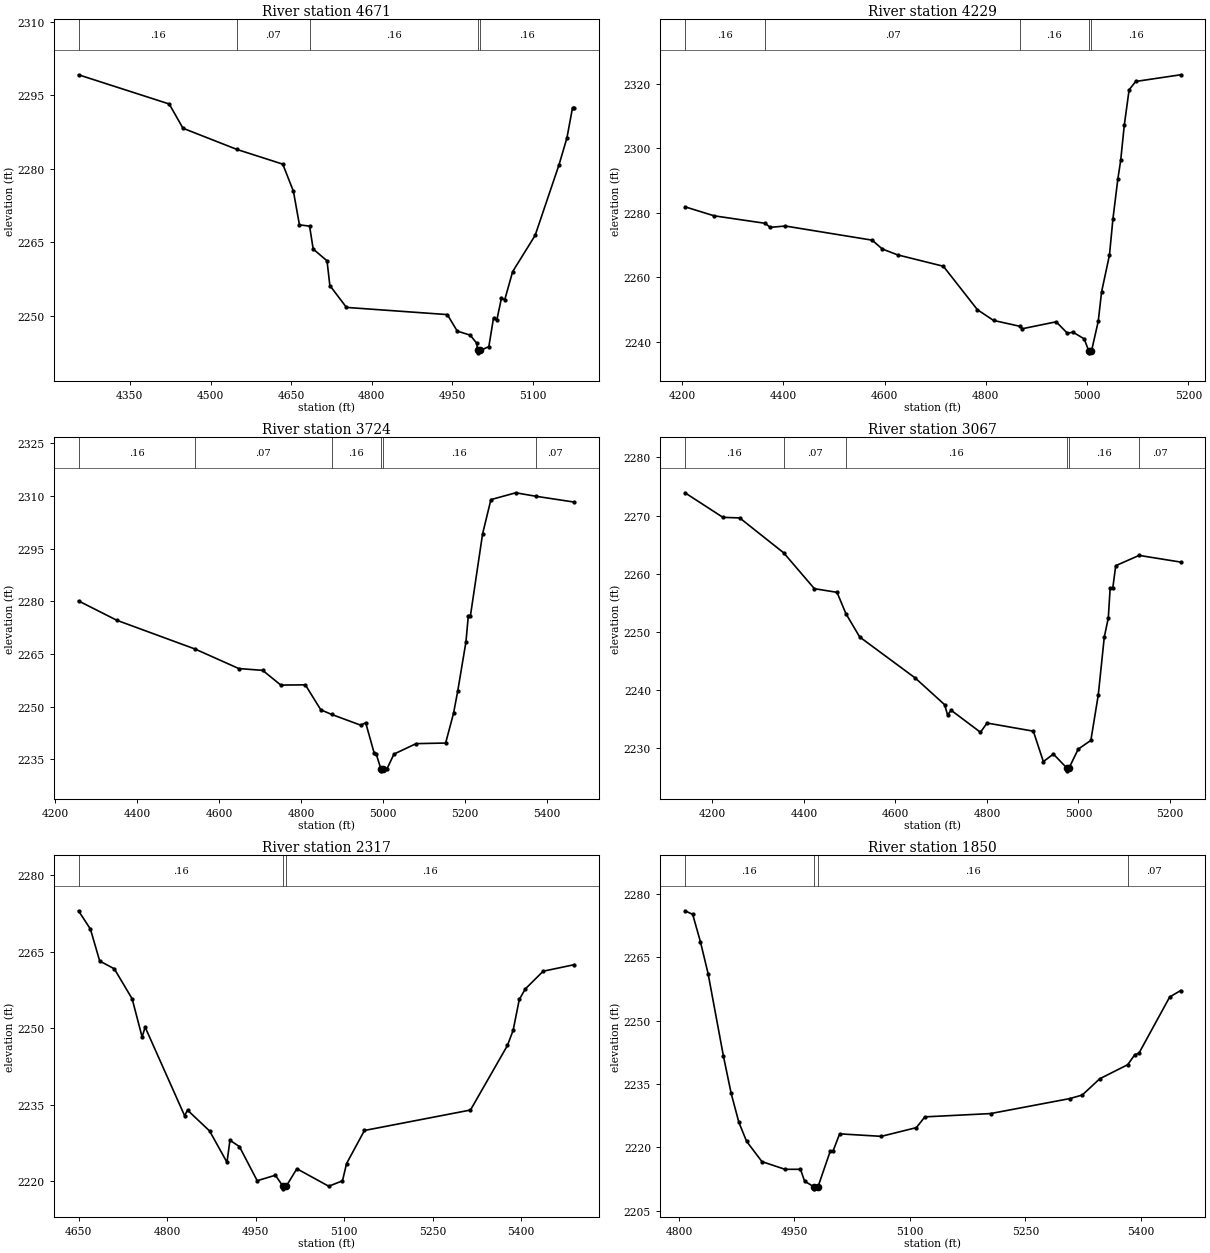
Type RM Length L Ch R = 1,4671,442,442,442
BEGIN DESCRIPTION:
elmc91
END DESCRIPTION:
XS GIS Cut Line= 3
      1501055.11      6771834.90      1500807.15      6771131.85
      1500705.02      6770988.02
#Sta/Elev= 30
  4254.5 2299.15  4423.2 2293.20  4448.8 2288.26  4549.3 2283.94  4634.4 2280.95
  4654.2 2275.43  4665.4 2268.59  4684.3 2268.32  4691.0 2263.66  4716.7 2261.26
  4722.0 2256.23  4752.9 2251.77  4940.5 2250.31  4958.9 2246.95  4982.9 2246.13
  4995.1 2244.49  4996.8 2243.02  4997.2 2242.52  5001.9 2243.02  5017.7 2243.78
  5026.4 2249.62  5032.5 2249.20  5041.1 2253.63  5047.3 2253.34  5062.0 2259.07
  5103.8 2266.44  5148.1 2280.78  5162.9 2286.27  5173.4 2292.46  5176.4 2292.46
#Mann=5,-1,0
  4254.5    0.16       0  4549.3    0.07       0  4684.3    0.16       0
  4996.8    0.07       0  5001.9    0.16       0
Bank Sta=4996.8,5001.9
Exp/Cntr=0.3,0.1

Type RM Length L Ch R = 1,4229,505,505,505
BEGIN DESCRIPTION:
elmc90
END DESCRIPTION:
XS GIS Cut Line= 3
      1501172.06      6771615.10      1501111.25      6771091.20
      1500905.43      6770688.91
#Sta/Elev= 30
  4205.5 2281.82  4263.0 2279.03  4364.1 2276.70  4373.7 2275.46  4403.9 2275.86
  4575.2 2271.48  4595.2 2268.76  4625.4 2266.93  4716.0 2263.39  4783.3 2249.92
  4815.1 2246.60  4867.2 2244.78  4872.2 2244.03  4938.8 2246.17  4961.2 2242.61
  4972.0 2242.97  4994.2 2240.89  5003.5 2237.05  5003.9 2236.55  5008.6 2237.05
  5022.0 2246.31  5028.6 2255.42  5044.2 2266.89  5051.0 2278.03  5060.8 2290.50
  5066.4 2296.25  5073.5 2307.17  5083.0 2318.08  5096.0 2320.68  5184.8 2322.75
#Mann=5,-1,0
  4205.5    0.16       0  4364.1    0.07       0  4867.2    0.16       0
  5003.5    0.07       0  5008.6    0.16       0
Bank Sta=5003.5,5008.6
Exp/Cntr=0.3,0.1

Type RM Length L Ch R = 1,3724,657,657,657
BEGIN DESCRIPTION:
elmc89
END DESCRIPTION:
XS GIS Cut Line= 3
      1501223.52      6771586.98      1501445.35      6770877.13
      1501522.87      6770417.62
#Sta/Elev= 30
  4256.3 2280.11  4349.9 2274.59  4540.2 2266.43  4647.5 2260.84  4705.7 2260.33
  4750.1 2256.13  4809.9 2256.20  4847.6 2249.09  4873.8 2247.78  4945.0 2244.71
  4957.2 2245.40  4977.5 2236.92  4982.7 2236.56  4994.4 2232.20  4994.8 2231.70
  4999.5 2232.20  5009.3 2232.31  5026.2 2236.47  5080.2 2239.45  5152.3 2239.62
  5171.5 2248.05  5181.7 2254.35  5201.9 2268.45  5207.7 2275.95  5212.7 2275.79
  5242.5 2299.22  5262.8 2308.97  5323.5 2310.92  5371.8 2309.94  5466.0 2308.27
#Mann=6,-1,0
  4256.3    0.16       0  4540.2    0.07       0  4873.8    0.16       0
  4994.4    0.07       0  4999.5    0.16       0  5371.8    0.07       0
Bank Sta=4994.4,4999.5
Exp/Cntr=0.3,0.1

Type RM Length L Ch R = 1,3067,750,750,750
BEGIN DESCRIPTION:
elmc88
END DESCRIPTION:
XS GIS Cut Line= 4
      1501321.71      6771512.20      1501753.88      6770976.96
      1501967.23      6770862.00      1501999.91      6770712.61
#Sta/Elev= 30
  4140.2 2273.92  4223.1 2269.69  4259.8 2269.59  4355.8 2263.59  4423.0 2257.41
  4472.5 2256.78  4491.8 2253.12  4522.1 2249.09  4643.6 2242.02  4707.6 2237.44
  4714.0 2235.69  4722.0 2236.47  4786.0 2232.69  4800.3 2234.28  4901.5 2232.88
  4923.4 2227.64  4945.3 2228.94  4974.5 2226.55  4974.9 2226.05  4979.6 2226.55
  4999.6 2229.79  5027.2 2231.29  5043.4 2239.11  5056.6 2249.10  5065.3 2252.35
  5069.4 2257.52  5075.1 2257.52  5081.6 2261.37  5132.7 2263.14  5223.4 2261.99
#Mann=6,-1,0
  4140.2    0.16       0  4355.8    0.07       0  4491.8    0.16       0
  4974.5    0.07       0  4979.6    0.16       0  5132.7    0.07       0
Bank Sta=4974.5,4979.6
Exp/Cntr=0.3,0.1

Type RM Length L Ch R = 1,2317,467,467,467
BEGIN DESCRIPTION:
elmc87
END DESCRIPTION:
XS GIS Cut Line= 3
      1502005.00      6771638.00      1501957.11      6771291.19
      1502023.36      6770805.89
#Sta/Elev= 30
  4649.9 2273.07  4670.1 2269.47  4685.8 2263.22  4710.5 2261.70  4740.8 2255.81
  4757.7 2248.32  4762.8 2250.26  4829.6 2232.91  4834.7 2233.98  4872.0 2229.91
  4901.5 2223.76  4906.5 2228.08  4922.5 2226.85  4952.7 2220.15  4983.5 2221.23
  4996.4 2219.06  4996.8 2218.56  5001.8 2219.06  5019.9 2222.50  5073.9 2219.07
  5097.2 2220.13  5104.1 2223.51  5134.4 2230.00  5314.1 2234.01  5376.7 2246.66
  5386.4 2249.65  5396.8 2255.68  5406.9 2257.73  5437.2 2261.22  5489.8 2262.50
#Mann=3,-1,0
  4649.9    0.16       0  4996.4    0.07       0  5001.8    0.16       0
Bank Sta=4996.4,5001.8
Exp/Cntr=0.3,0.1

Type RM Length L Ch R = 1,1850,441,441,441
BEGIN DESCRIPTION:
elmc86
END DESCRIPTION:
XS GIS Cut Line= 3
      1502255.00      6771537.97      1502248.83      6771345.86
      1502054.99      6770937.98
#Sta/Elev= 30
  4807.8 2276.04  4817.8 2275.19  4827.8 2268.75  4837.8 2261.18  4857.8 2241.57
  4867.8 2232.79  4877.8 2225.95  4887.8 2221.46  4907.8 2216.64  4937.8 2214.82
  4957.8 2214.83  4963.2 2212.01  4975.1 2210.70  4975.6 2210.20  4980.6 2210.70
  4996.4 2219.08  5000.0 2219.08  5008.7 2223.22  5062.8 2222.63  5108.3 2224.69
  5119.4 2227.24  5204.7 2228.02  5307.6 2231.57  5323.8 2232.41  5346.6 2236.27
  5382.9 2239.60  5392.0 2241.96  5397.5 2242.33  5437.4 2255.63  5451.6 2257.15
#Mann=4,-1,0
  4807.8    0.16       0  4975.1    0.07       0  4980.6    0.16       0
  5382.9    0.07       0
Bank Sta=4975.1,4980.6
Exp/Cntr=0.3,0.1