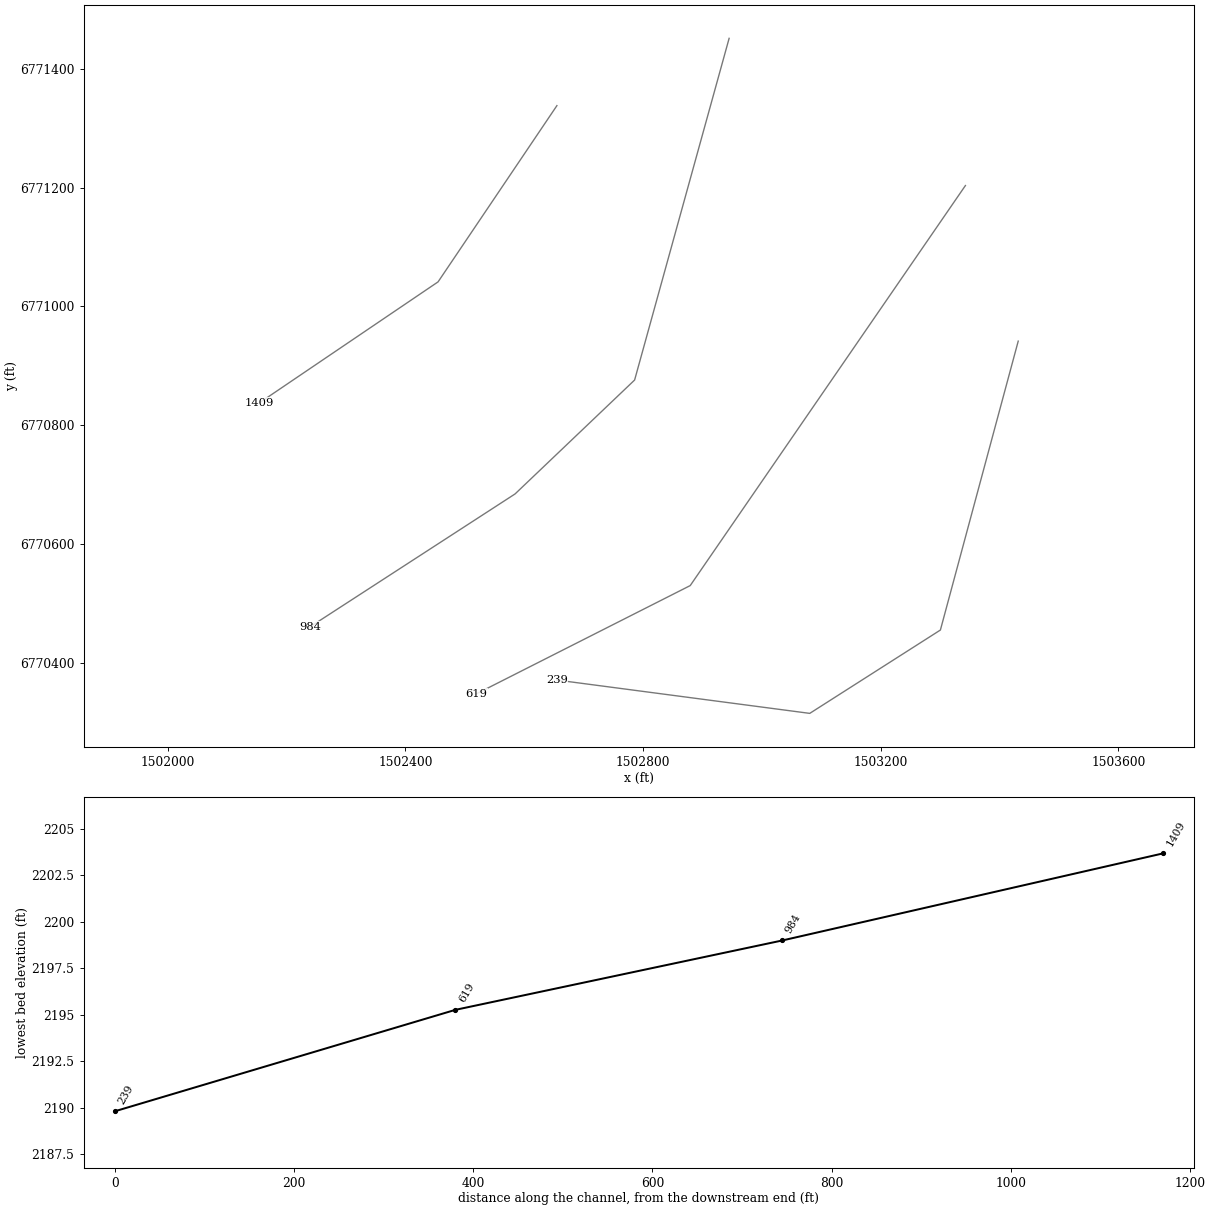
HEC-RAS study Elm 38.prj: Elm 38 Base Level Engineering

--- Elm 38.g01 (geometry) --- (continued)

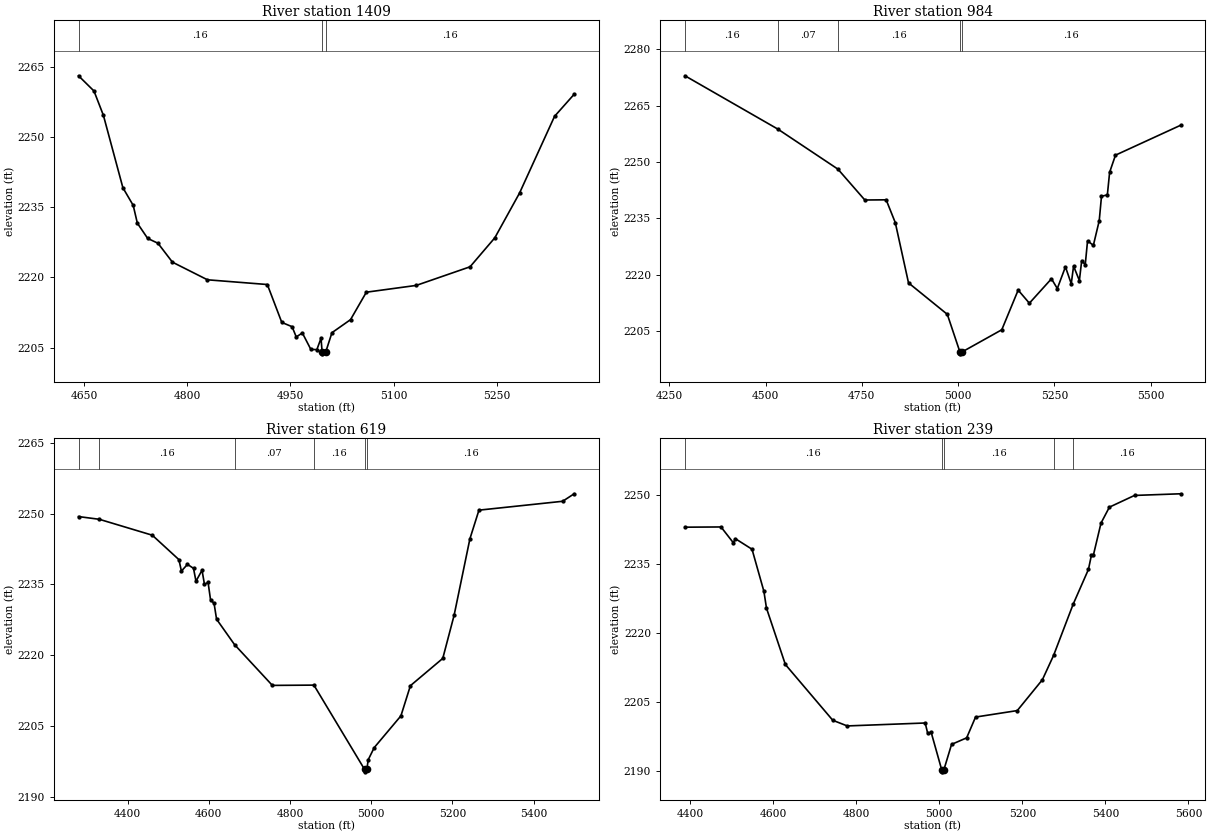
Type RM Length L Ch R = 1,1409,425,425,425
BEGIN DESCRIPTION:
elmc85
END DESCRIPTION:
XS GIS Cut Line= 3
      1502655.02      6771338.03      1502455.08      6771041.31
      1502154.97      6770837.98
#Sta/Elev= 30
  4642.2 2263.12  4664.7 2259.86  4678.4 2254.65  4706.7 2239.18  4721.7 2235.41
  4727.7 2231.61  4742.7 2228.35  4757.7 2227.31  4778.7 2223.27  4829.6 2219.50
  4916.6 2218.49  4937.6 2210.39  4952.6 2209.47  4958.6 2207.29  4967.5 2208.13
  4979.9 2204.60  4988.6 2204.58  4994.6 2206.99  4996.2 2204.17  4996.7 2203.67
  5001.7 2204.17  5010.5 2208.19  5037.5 2210.98  5060.5 2216.85  5133.0 2218.30
  5211.2 2222.28  5247.2 2228.48  5283.1 2238.04  5334.0 2254.45  5362.5 2259.17
#Mann=3,-1,0
  4642.2    0.16       0  4996.2    0.07       0  5001.7    0.16       0
Bank Sta=4996.2,5001.7
Exp/Cntr=0.3,0.1

Type RM Length L Ch R = 1,984,365,365,365
BEGIN DESCRIPTION:
elmc316
END DESCRIPTION:
XS GIS Cut Line= 4
      1502944.82      6771451.35      1502785.79      6770876.03
      1502584.66      6770684.25      1502239.26      6770460.21
#Sta/Elev= 30
  4291.0 2272.90  4532.3 2258.71  4687.9 2248.09  4757.8 2239.88  4813.2 2239.93
  4836.9 2233.86  4871.2 2217.85  4971.9 2209.49  5004.6 2199.49  5005.0 2198.99
  5010.1 2199.49  5113.3 2205.39  5155.8 2215.93  5184.9 2212.45  5242.2 2218.94
  5257.4 2216.35  5278.5 2222.11  5293.6 2217.62  5299.6 2222.30  5314.7 2218.48
  5320.7 2223.76  5329.9 2222.69  5335.9 2229.01  5351.0 2227.84  5366.2 2234.37
  5372.1 2240.87  5387.3 2241.24  5393.2 2247.25  5408.4 2251.80  5577.5 2259.75
#Mann=5,-1,0
  4291.0    0.16       0  4532.3    0.07       0  4687.9    0.16       0
  5004.6    0.07       0  5010.1    0.16       0
Bank Sta=5004.6,5010.1
Exp/Cntr=0.3,0.1

Type RM Length L Ch R = 1,619,380,380,380
BEGIN DESCRIPTION:
elmc315
END DESCRIPTION:
XS GIS Cut Line= 3
      1503342.43      6771203.48      1502879.34      6770529.90
      1502519.57      6770347.67
#Sta/Elev= 30
  4279.3 2249.36  4330.6 2248.78  4461.0 2245.41  4526.6 2240.23  4532.7 2237.80
  4547.6 2239.23  4562.5 2238.39  4568.6 2235.66  4583.5 2237.98  4589.5 2235.00
  4598.4 2235.39  4604.4 2231.76  4613.2 2230.94  4619.3 2227.61  4663.5 2222.23
  4756.7 2213.58  4859.0 2213.64  4983.9 2195.76  4984.3 2195.26  4989.5 2195.76
  4992.7 2197.81  5007.6 2200.40  5073.3 2207.12  5096.7 2213.52  5176.4 2219.30
  5204.3 2228.43  5243.2 2244.64  5265.5 2250.72  5471.6 2252.60  5500.0 2254.19
#Mann=6,-1,0
  4279.3    0.07       0  4330.6    0.16       0  4663.5    0.07       0
  4859.0    0.16       0  4983.9    0.07       0  4989.5    0.16       0
Bank Sta=4983.9,4989.5
Exp/Cntr=0.3,0.1

Type RM Length L Ch R = 1,239,0,0,0
BEGIN DESCRIPTION:
elmc314
END DESCRIPTION:
XS GIS Cut Line= 4
      1503431.29      6770941.52      1503300.32      6770455.06
      1503080.48      6770314.73      1502654.85      6770370.86
#Sta/Elev= 30
  4387.4 2243.05  4474.2 2243.10  4503.8 2239.67  4508.9 2240.54  4548.9 2238.25
  4577.5 2229.09  4583.7 2225.44  4629.2 2213.17  4743.4 2201.03  4778.2 2199.80
  4966.0 2200.44  4972.0 2198.21  4980.5 2198.38  5005.6 2190.31  5006.0 2189.81
  5011.2 2190.31  5029.5 2195.78  5065.9 2197.21  5087.3 2201.73  5187.8 2203.14
  5248.3 2209.85  5275.3 2215.15  5322.3 2226.26  5359.2 2233.85  5366.3 2236.91
  5371.3 2237.03  5389.5 2243.94  5409.7 2247.41  5470.2 2249.96  5581.3 2250.32
#Mann=5,-1,0
  4387.4    0.16       0  5005.6    0.07       0  5011.2    0.16       0
  5275.3    0.07       0  5322.3    0.16       0
Bank Sta=5005.6,5011.2
Exp/Cntr=0.3,0.1

Chan Stop Cuts=-1