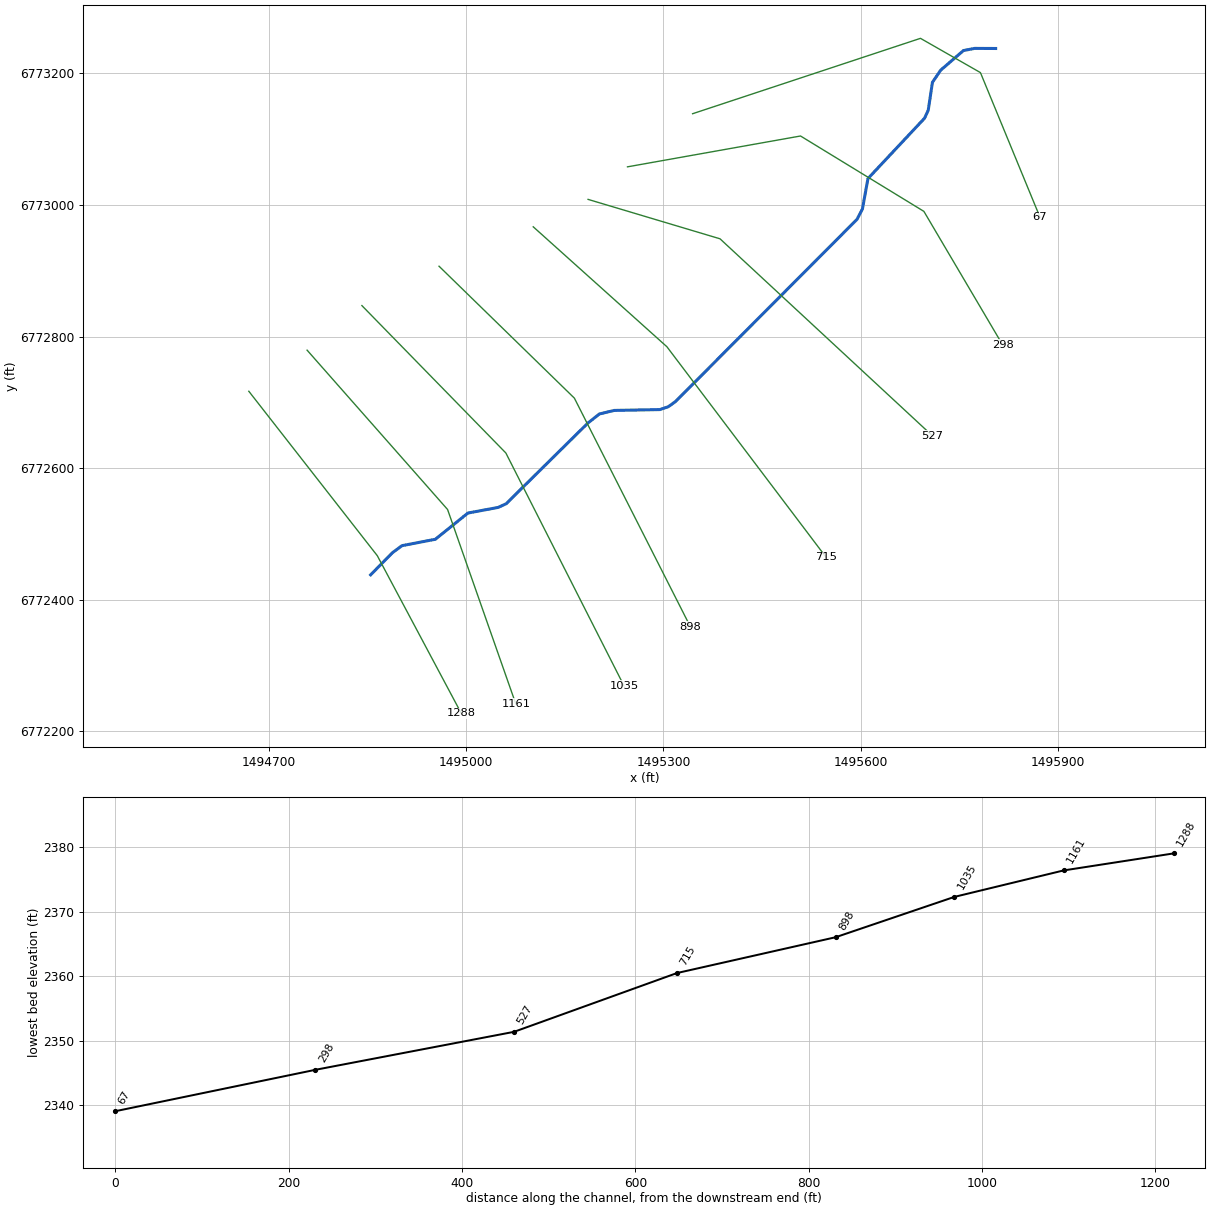
--- Elm 39.prj (project) ---

Proj Title=Elm 39 Base Level Engineering
Current Plan=p01
Default Exp/Contr=0.3,0.1
English Units
Geom File=g01
Flow File=f01
Plan File=p01
BEGIN DESCRIPTION:
Elm 39
END DESCRIPTION:

--- Elm 39.p01 (plan) ---

Plan Title=Multiple Run
Short Identifier=Multiple
Geom File=g01
Flow File=f01
Subcritical Flow
K Sum by GR= 0
Std Step Tol= 0.01
Critical Tol= 0.01
Num of Std Step Trials= 20
Max Error Tol= 0.3
Flow Tol Ratio= 0.001
Split Flow NTrial= 30
Split Flow Tol= 0.02
Split Flow Ratio= 0.02
Log Output Level= 0
Friction Slope Method= 1
Unsteady Friction Slope Method= 2
Unsteady Bridges Friction Slope Method= 1
Parabolic Critical Depth
Global Vel Dist=  1 , 1 , 1
Global Log Level= 0
CheckData=True
Encroach Param= -1, 0, 0, 0
BEGIN DESCRIPTION:
Multiple Run
END DESCRIPTION:

--- Elm 39.f01 (steady flow) ---

Flow Title=Multiple
Number of Profiles=7
Profile Names=10-year,25-year,50-year,1pct_min,100-year,1pct_plu,500-year
River Rch & RM= Elm 39,Reach-1,1288
      92     120     143     106     169     233     239
Boundary for River Rch & Prof#=Elm 39,Reach-1,1
Up Type=0
Dn Type=3
Dn Slope=0.005
Boundary for River Rch & Prof#=Elm 39,Reach-1,2
Up Type=0
Dn Type=3
Dn Slope=0.005
Boundary for River Rch & Prof#=Elm 39,Reach-1,3
Up Type=0
Dn Type=3
Dn Slope=0.005
Boundary for River Rch & Prof#=Elm 39,Reach-1,4
Up Type=0
Dn Type=3
Dn Slope=0.005
Boundary for River Rch & Prof#=Elm 39,Reach-1,5
Up Type=0
Dn Type=3
Dn Slope=0.005
Boundary for River Rch & Prof#=Elm 39,Reach-1,6
Up Type=0
Dn Type=3
Dn Slope=0.005
Boundary for River Rch & Prof#=Elm 39,Reach-1,7
Up Type=0
Dn Type=3
Dn Slope=0.005

--- Elm 39.g01 (geometry) ---

Geom Title=Existing Conditions

River Reach=Elm 39,Reach-1
Reach XY= 28
      1494855.00      6772438.00      1494888.07      6772471.59
      1494902.64      6772482.33      1494953.33      6772492.04
      1495002.81      6772531.90      1495048.97      6772540.50
      1495061.06      6772546.14      1495122.95      6772607.26
      1495184.85      6772668.37      1495202.57      6772682.48
      1495225.06      6772687.87      1495294.52      6772689.17
      1495307.43      6772693.52      1495318.30      6772701.40
      1495387.28      6772770.63      1495456.26      6772839.86
      1495525.24      6772909.09      1495594.22      6772978.32
      1495602.47      6772994.05      1495610.87      6773040.28
      1495653.85      6773086.12      1495696.83      6773131.97
      1495702.48      6773144.07      1495708.86      6773186.54
      1495721.38      6773205.03      1495756.03      6773234.86
      1495772.95      6773238.15      1495805.00      6773238.00

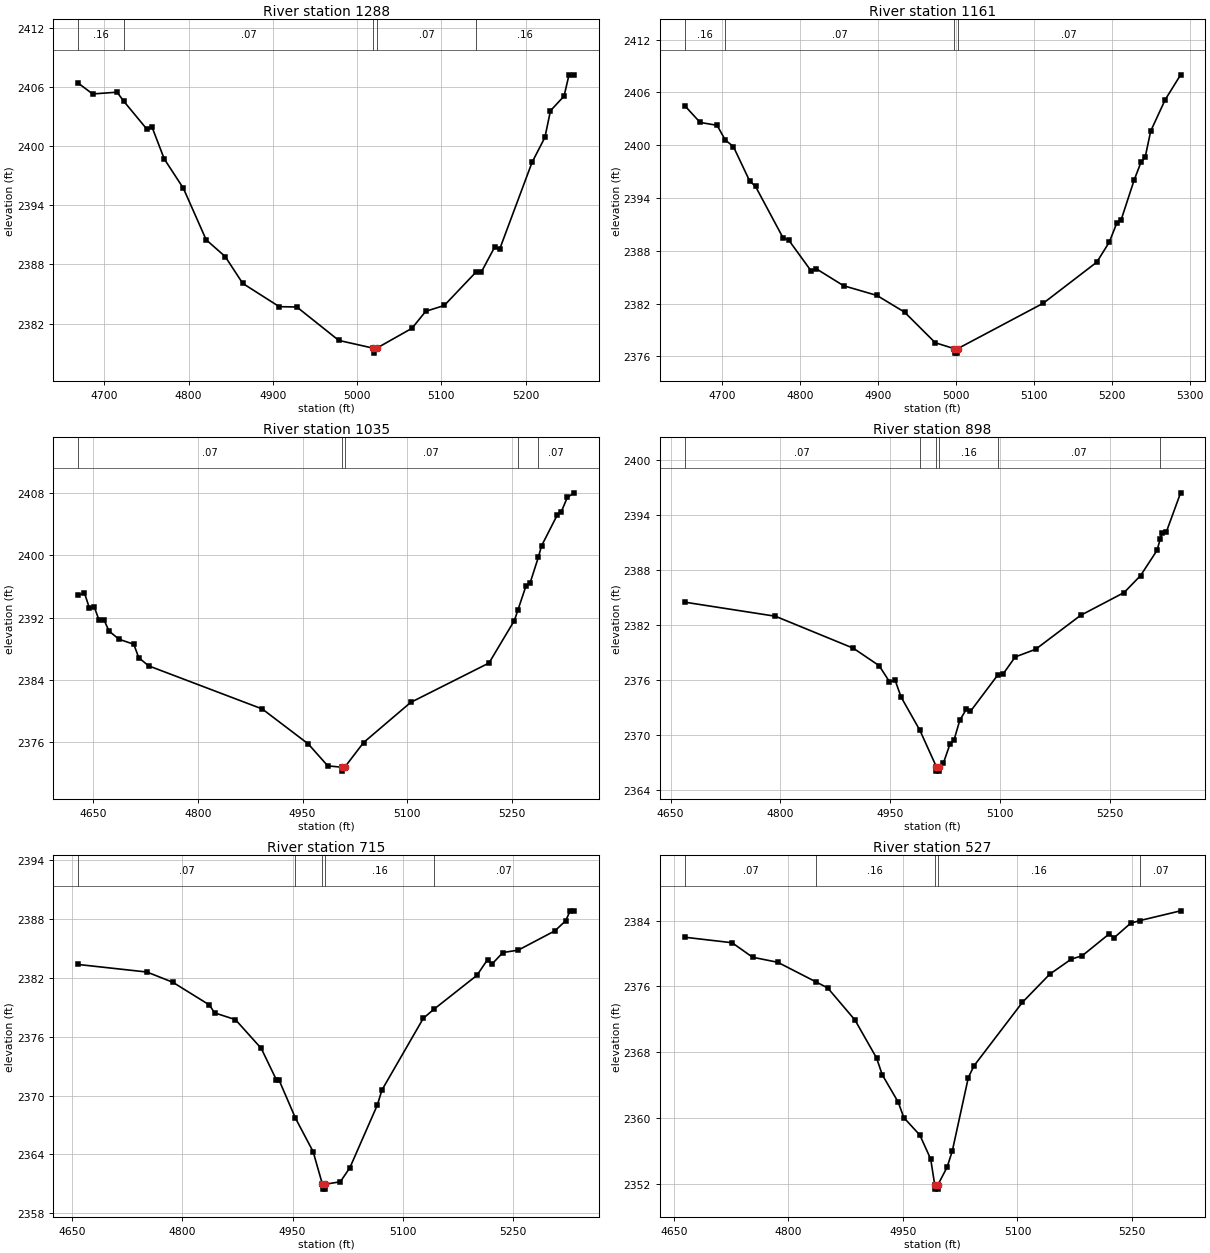
Type RM Length L Ch R = 1,1288,127,127,127
BEGIN DESCRIPTION:
elmc326
END DESCRIPTION:
XS GIS Cut Line= 3
      1494669.83      6772717.00      1494865.16      6772466.98
      1494992.75      6772227.42
#Sta/Elev= 30
  4669.0 2406.39  4686.1 2405.29  4715.1 2405.47  4723.0 2404.56  4750.4 2401.73
  4756.7 2401.91  4771.2 2398.69  4793.8 2395.73  4820.9 2390.50  4843.5 2388.80
  4864.3 2386.08  4907.7 2383.72  4928.5 2383.69  4978.3 2380.30  5019.3 2379.51
  5019.6 2379.01  5023.3 2379.51  5065.2 2381.53  5081.5 2383.25  5103.5 2383.84
  5141.3 2387.24  5147.4 2387.21  5163.7 2389.82  5169.4 2389.58  5207.7 2398.35
  5223.0 2400.89  5229.6 2403.59  5245.7 2405.07  5251.6 2407.23  5257.7 2407.18
#Mann=5,-1,0
  4669.0    0.16       0  4723.0    0.07       0  5019.3    0.07       0
  5023.3    0.07       0  5141.3    0.16       0
Bank Sta=5019.3,5023.3
Exp/Cntr=0.3,0.1

Type RM Length L Ch R = 1,1161,126,126,126
BEGIN DESCRIPTION:
elmc325
END DESCRIPTION:
XS GIS Cut Line= 3
      1494758.38      6772779.49      1494971.93      6772537.29
      1495075.63      6772241.75
#Sta/Elev= 30
  4652.1 2404.50  4671.9 2402.59  4693.7 2402.26  4704.1 2400.60  4714.6 2399.84
  4735.4 2395.94  4743.0 2395.31  4778.1 2389.50  4785.7 2389.20  4814.1 2385.73
  4820.8 2385.96  4855.9 2384.03  4898.6 2382.93  4934.1 2381.03  4973.5 2377.55
  4998.1 2376.87  4998.3 2376.37  5001.8 2376.37  5002.1 2376.87  5112.0 2382.04
  5180.7 2386.71  5196.8 2389.00  5206.4 2391.17  5211.7 2391.46  5228.6 2396.04
  5237.4 2398.07  5242.7 2398.62  5249.8 2401.60  5268.4 2405.17  5288.2 2408.00
#Mann=4,-1,0
  4652.1    0.16       0  4704.1    0.07       0  4998.1    0.07       0
  5002.1    0.07       0
Bank Sta=4998.1,5002.1
Exp/Cntr=0.3,0.1

Type RM Length L Ch R = 1,1035,137,137,137
BEGIN DESCRIPTION:
elmc324
END DESCRIPTION:
XS GIS Cut Line= 3
      1494841.71      6772847.20      1495060.47      6772623.23
      1495240.06      6772269.26
#Sta/Elev= 30
  4628.9 2394.86  4637.8 2395.18  4644.8 2393.27  4651.9 2393.37  4658.9 2391.64
  4666.1 2391.66  4673.0 2390.28  4687.2 2389.23  4708.5 2388.58  4715.5 2386.86
  4729.6 2385.81  4892.4 2380.26  4958.2 2375.77  4986.1 2372.95  5006.4 2372.77
  5006.6 2372.27  5010.4 2372.77  5037.5 2375.95  5104.8 2381.10  5217.0 2386.17
  5253.3 2391.63  5258.4 2392.99  5269.9 2396.07  5275.6 2396.40  5287.7 2399.78
  5292.2 2401.23  5314.5 2405.16  5320.1 2405.53  5329.1 2407.46  5338.9 2408.05
#Mann=5,-1,0
  4628.9    0.07       0  5006.4    0.07       0  5010.4    0.07       0
  5258.4    0.16       0  5287.7    0.07       0
Bank Sta=5006.4,5010.4
Exp/Cntr=0.3,0.1

Type RM Length L Ch R = 1,898,183,183,183
BEGIN DESCRIPTION:
elmc323
END DESCRIPTION:
XS GIS Cut Line= 3
      1494958.92      6772907.07      1495164.64      6772706.56
      1495340.87      6772359.28
#Sta/Elev= 30
  4669.3 2384.49  4793.1 2382.95  4899.3 2379.46  4934.6 2377.55  4948.7 2375.80
  4956.6 2375.93  4964.5 2374.13  4990.3 2370.47  5012.6 2366.52  5012.9 2366.02
  5016.4 2366.02  5016.6 2366.52  5022.2 2366.87  5031.3 2368.98  5036.9 2369.45
  5044.7 2371.58  5053.5 2372.77  5059.1 2372.54  5096.8 2376.56  5103.7 2376.63
  5120.3 2378.50  5148.2 2379.34  5209.4 2383.04  5268.9 2385.54  5291.4 2387.40
  5313.8 2390.15  5318.0 2391.34  5320.7 2392.10  5326.3 2392.12  5346.0 2396.44
#Mann=6,-1,0
  4669.3    0.07       0  4990.3    0.16       0  5012.6    0.07       0
  5016.6    0.16       0  5096.8    0.07       0  5318.0    0.16       0
Bank Sta=5012.6,5016.6
Exp/Cntr=0.3,0.1

Type RM Length L Ch R = 1,715,188,188,188
BEGIN DESCRIPTION:
elmc322
END DESCRIPTION:
XS GIS Cut Line= 3
      1495102.15      6772966.96      1495305.26      6772784.69
      1495547.46      6772464.35
#Sta/Elev= 30
  4658.4 2383.37  4751.9 2382.60  4787.0 2381.56  4836.9 2379.24  4843.8 2378.44
  4872.2 2377.75  4907.3 2374.82  4927.8 2371.63  4931.3 2371.63  4953.9 2367.70
  4977.9 2364.29  4990.5 2360.97  4990.8 2360.47  4994.3 2360.47  4994.5 2360.97
  5014.9 2361.22  5027.9 2362.66  5065.1 2369.02  5071.6 2370.59  5127.8 2377.89
  5141.9 2378.79  5200.6 2382.26  5215.1 2383.86  5221.4 2383.43  5236.0 2384.59
  5256.8 2384.83  5306.7 2386.80  5321.3 2387.82  5327.5 2388.84  5332.9 2388.84
#Mann=5,-1,0
  4658.4    0.07       0  4953.9    0.16       0  4990.5    0.07       0
  4994.5    0.16       0  5141.9    0.07       0
Bank Sta=4990.5,4994.5
Exp/Cntr=0.3,0.1

Type RM Length L Ch R = 1,527,229,229,229
BEGIN DESCRIPTION:
elmc321
END DESCRIPTION:
XS GIS Cut Line= 3
      1495185.46      6773008.65      1495385.99      6772948.75
      1495708.91      6772649.27
#Sta/Elev= 30
  4664.0 2381.99  4726.1 2381.32  4752.9 2379.56  4786.0 2378.94  4836.0 2376.56
  4851.4 2375.82  4887.1 2371.92  4915.4 2367.30  4922.8 2365.27  4943.8 2361.93
  4951.1 2360.05  4972.1 2357.93  4986.3 2355.01  4991.6 2351.86  4991.9 2351.36
  4995.4 2351.36  4995.6 2351.86  5007.8 2354.03  5014.6 2356.00  5035.6 2364.93
  5043.0 2366.35  5106.5 2374.08  5142.2 2377.49  5170.5 2379.33  5184.7 2379.73
  5219.8 2382.37  5226.7 2381.94  5248.2 2383.69  5260.6 2384.02  5313.7 2385.20
#Mann=5,-1,0
  4664.0    0.07       0  4836.0    0.16       0  4991.6    0.07       0
  4995.6    0.16       0  5260.6    0.07       0
Bank Sta=4991.6,4995.6
Exp/Cntr=0.3,0.1

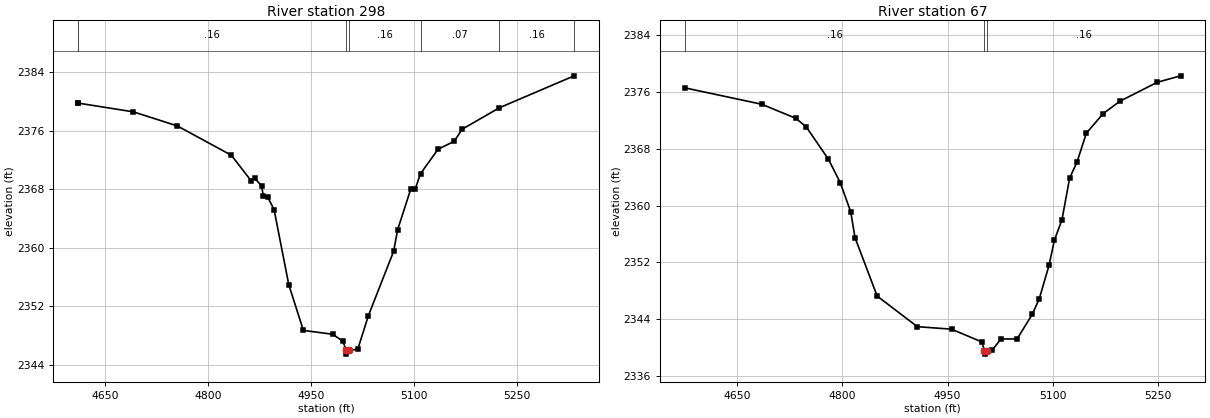
Type RM Length L Ch R = 1,298,231,231,231
BEGIN DESCRIPTION:
elmc320
END DESCRIPTION:
XS GIS Cut Line= 4
      1495245.39      6773058.13      1495508.39      6773105.00
      1495695.89      6772990.42      1495815.68      6772787.29
#Sta/Elev= 30
  4611.3 2379.78  4611.4 2379.78  4691.6 2378.59  4755.6 2376.67  4834.4 2372.66
  4863.4 2369.16  4868.5 2369.52  4878.4 2368.48  4881.3 2367.02  4887.2 2366.97
  4896.7 2365.24  4918.1 2354.99  4939.4 2348.72  4982.0 2348.20  4997.4 2347.22
  5001.4 2345.98  5001.6 2345.48  5005.4 2345.98  5018.7 2346.15  5034.2 2350.75
  5070.9 2359.52  5076.8 2362.49  5095.7 2367.98  5102.2 2367.98  5110.1 2370.14
  5135.8 2373.49  5159.0 2374.55  5170.9 2376.22  5225.2 2379.15  5334.0 2383.51
#Mann=7,-1,0
  4611.3    0.07       0  4611.4    0.16       0  5001.4    0.07       0
  5005.4    0.16       0  5110.1    0.07       0  5225.2    0.16       0
  5334.0    0.07       0
Bank Sta=5001.4,5005.4
Exp/Cntr=0.3,0.1

Type RM Length L Ch R = 1,67,0,0,0
BEGIN DESCRIPTION:
elmc319
END DESCRIPTION:
XS GIS Cut Line= 4
      1495344.32      6773138.85      1495690.68      6773253.44
      1495781.82      6773201.35      1495872.37      6772981.46
#Sta/Elev= 30
  4575.0 2376.62  4685.0 2374.30  4733.7 2372.31  4748.5 2371.10  4780.2 2366.53
  4796.9 2363.26  4811.9 2359.14  4818.0 2355.50  4849.6 2347.25  4907.0 2342.93
  4955.7 2342.58  4998.9 2340.78  5002.7 2339.56  5002.9 2339.06  5006.7 2339.56
  5013.9 2339.65  5026.3 2341.19  5049.3 2341.21  5070.9 2344.66  5080.9 2346.86
  5094.8 2351.56  5102.5 2355.13  5113.3 2358.00  5124.2 2363.87  5134.9 2366.19
  5148.1 2370.22  5172.1 2372.98  5196.0 2374.73  5249.3 2377.40  5282.6 2378.31
#Mann=3,-1,0
  4575.0    0.16       0  5002.7    0.07       0  5006.7    0.16       0
Bank Sta=5002.7,5006.7
Exp/Cntr=0.3,0.1

Chan Stop Cuts=-1