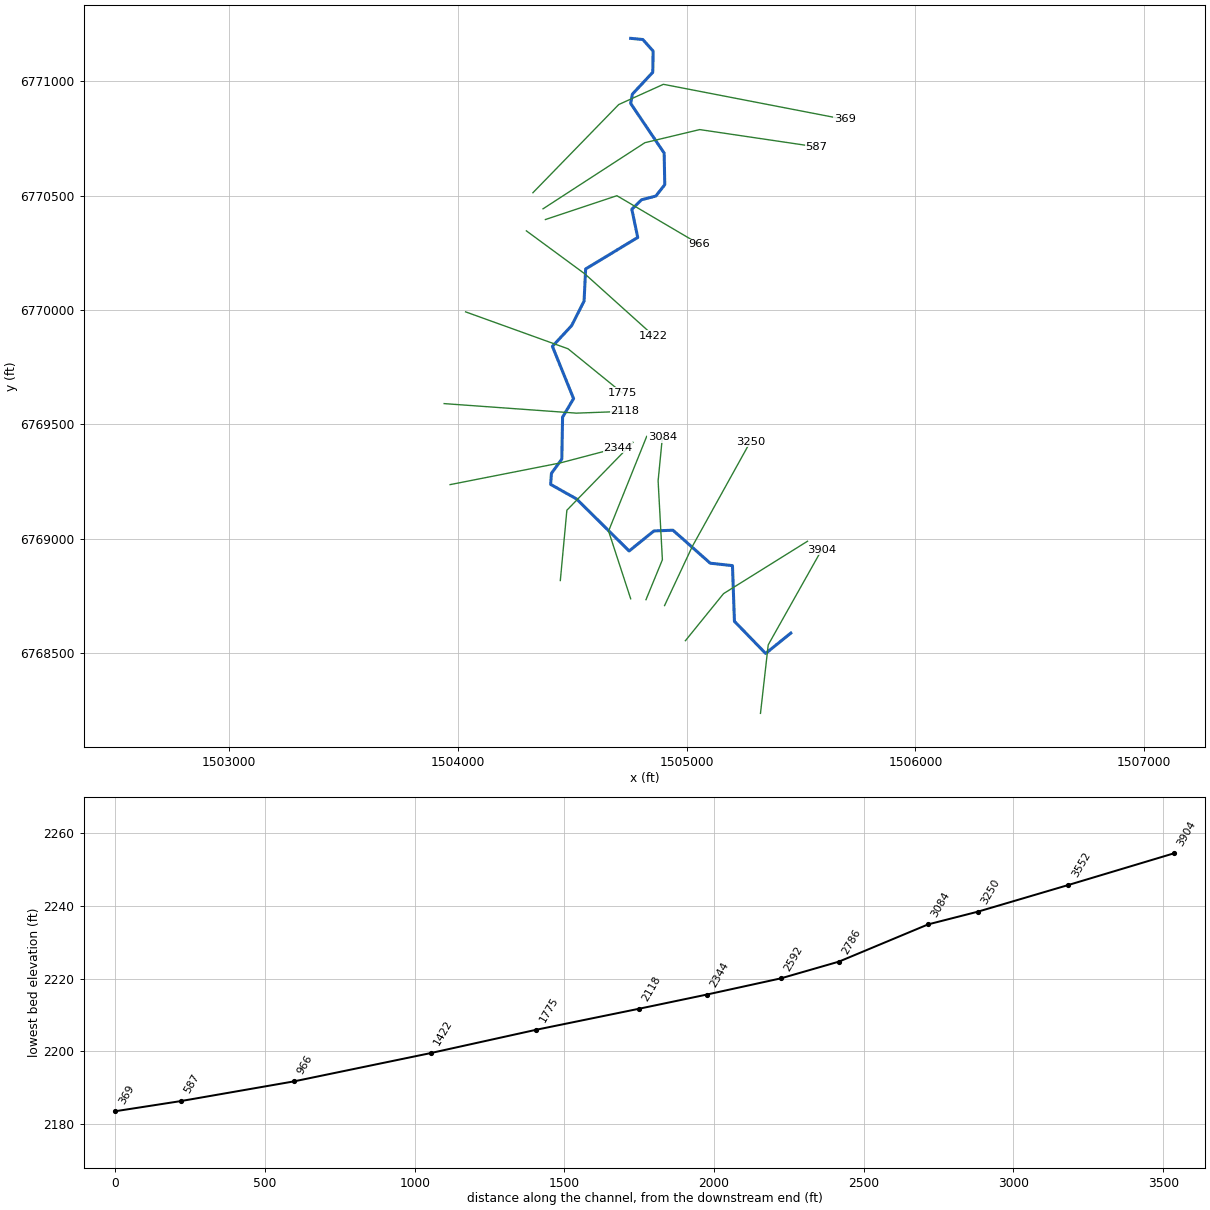
--- Elm 40.prj (project) ---

Proj Title=Elm 40 Base Level Engineering
Current Plan=p01
Default Exp/Contr=0.3,0.1
English Units
Geom File=g01
Flow File=f01
Plan File=p01
Y Axis Title=Elevation
X Axis Title(PF)=Main Channel Distance
X Axis Title(XS)=Station
BEGIN DESCRIPTION:
Elm 40
END DESCRIPTION:
DSS Export Rating Curves= 0
DSS Export Rating Curve Sorted= 0
DSS Export Volume Flow Curves= 0
DXF OffsetX= 0
DXF OffsetY= 0
DXF ScaleX= 1
DXF ScaleY= 10

--- Elm 40.p01 (plan) ---

Plan Title=Multiple Run
Program Version=4.10
Short Identifier=Multiple
Geom File=g01
Flow File=f01
Subcritical Flow
K Sum by GR= 0
Std Step Tol= 0.01
Critical Tol= 0.01
Num of Std Step Trials= 20
Max Error Tol= 0.3
Flow Tol Ratio= 0.001
Split Flow NTrial= 30
Split Flow Tol= 0.02
Split Flow Ratio= 0.02
Log Output Level= 0
Friction Slope Method= 1
Unsteady Friction Slope Method= 2
Unsteady Bridges Friction Slope Method= 1
Parabolic Critical Depth
Global Vel Dist= 1 , 1 , 1
Global Log Level= 0
CheckData=True
Encroach Param=-1 ,0,0, 0
BEGIN DESCRIPTION:
Multiple Run
END DESCRIPTION:
Computation Interval=1HOUR
Output Interval=1HOUR
Run HTab= 0
Run UNet= 0
Run PostProcess= 0
Run WQNet= 0
UNET Theta= 1
UNET Theta Warmup= 1
UNET ZTol= 0.02
UNET ZSATol= 0.05
UNET MxIter= 20
UNET MaxInSteps= 0
UNET DtIC= 0
UNET DtMin= 0
UNET MaxCRTS= 20
UNET WFStab= 2
UNET SFStab= 1
UNET WFX= 1
UNET SFX= 1
UNET DSS MLevel= 4
UNET DZMax Abort= 100
UNET Convert EG Bridges= 0
UNET Use Existing IB Tables=-1
UNET Froude Reduction=False
UNET Froude Limit= 1
UNET Froude Power= 10
UNET Time Slicing=0,0, 5
UNET Junction Losses=0
Instantaneous Interval=1HOUR
Write IC File= 0
Write IC File at Sim End=0
Echo Input=False
Echo Parameters=False
Echo Output=False
Write Detailed= 0
WQ AD Non Conservative
WQ ULTIMATE=-1
WQ Max Comp Step=1HOUR
WQ Output Interval=15MIN
WQ Output Selected Increments= 0
WQ Output face flow=0
WQ Output face velocity=0
WQ Output face area=0
WQ Output face dispersion=0
WQ Output cell volume=0
WQ Output cell surface area=0
WQ Output cell continuity=0
WQ Output cumulative cell continuity=0
WQ Output face conc=0
WQ Output face dconc_dx=0
WQ Output face courant=0
WQ Output face peclet=0
WQ Output face adv mass=0
WQ Output face disp mass=0
WQ Output cell mass=0
WQ Output cell source sink temp=0
WQ Output cell source sink nsm=0
WQ Output MaxMinRange=-1
WQ Daily Max Min Mean=-1
WQ Daily Range=0
WQ Daily Time=0
WQ Create Restart=0
WQ Fixed Restart=0
WQ System Summary=0
WQ Use Fixed Temperature=0
Sorting and Armoring Iterations= 10
XS Update Threshold= 0.02
Hydraulics Update Threshold= 0.02
Energy Slope Method= 1
Volume Change Method= 0
XS Weighting Method= 0
Number of US Weighted Cross Sections= 1
Number of DS Weighted Cross Sections= 1
Upstream XS Weight=0.25
Main XS Weight=0.5
Downstream XS Weight=0.25
Number of DS XS's Weighted with US Boundary= 1
Upstream Boundary Weight= 1
Weight of XSs Associated with US Boundary= 0
Number of US XS's Weighted with DS Boundary= 1
Downstream Boundary Weight= 0.5
Weight of XSs Associated with DS Boundary= 0.5
Sediment Output Level= 4
Mass or Volume Output= 0
Output Increment Type= 1
Profile and TS Output Increment= 10
XS Output Flag= 0
XS Output Increment= 10
Disregard all LS=0
Disregard all Conn=0
Disregard all Breaches=0
Disregard all Pumps=0

--- Elm 40.f01 (steady flow) ---

Flow Title=Multiple
Number of Profiles=7
Profile Names=10-year,25-year,50-year,1pct_min,100-year,1pct_plu,500-year
River Rch & RM= Elm 40,Reach-1,3904
     171     236     290     221     355     488     538
River Rch & RM= Elm 40,Reach-1,2344
     296     422     530     413     662     911    1050
Boundary for River Rch & Prof#=Elm 40,Reach-1,1
Up Type=0
Dn Type=3
Dn Slope=0.005
Boundary for River Rch & Prof#=Elm 40,Reach-1,2
Up Type=0
Dn Type=3
Dn Slope=0.005
Boundary for River Rch & Prof#=Elm 40,Reach-1,3
Up Type=0
Dn Type=3
Dn Slope=0.005
Boundary for River Rch & Prof#=Elm 40,Reach-1,4
Up Type=0
Dn Type=3
Dn Slope=0.005
Boundary for River Rch & Prof#=Elm 40,Reach-1,5
Up Type=0
Dn Type=3
Dn Slope=0.005
Boundary for River Rch & Prof#=Elm 40,Reach-1,6
Up Type=0
Dn Type=3
Dn Slope=0.005
Boundary for River Rch & Prof#=Elm 40,Reach-1,7
Up Type=0
Dn Type=3
Dn Slope=0.005

--- Elm 40.g01 (geometry) ---

Geom Title=Existing Conditions
Program Version=4.10

River Reach=Elm 40          ,Reach-1
Reach XY= 30
        1505455.        6768588.        1505345.      6768498.92
      1505208.54      6768639.46      1505199.97      6768882.92
      1505102.64      6768893.55      1504939.78      6769037.76
       1504856.5      6769034.52      1504748.33      6768946.96
      1504518.23      6769174.43        1504405.        6769238.
      1504408.65      6769286.49      1504453.88      6769348.46
      1504457.29      6769532.07       1504505.4        6769613.
      1504412.81      6769841.41      1504496.82      6769931.94
      1504551.24      6770039.56      1504558.08       6770179.7
      1504785.86      6770317.58      1504760.01      6770440.53
      1504802.41      6770482.24      1504865.04      6770498.63
      1504904.03      6770548.29      1504901.26      6770686.44
       1504754.9      6770903.36      1504762.48      6770944.04
      1504851.53       6771039.5      1504853.17      6771132.27
      1504807.95      6771182.87        1504755.        6771188.

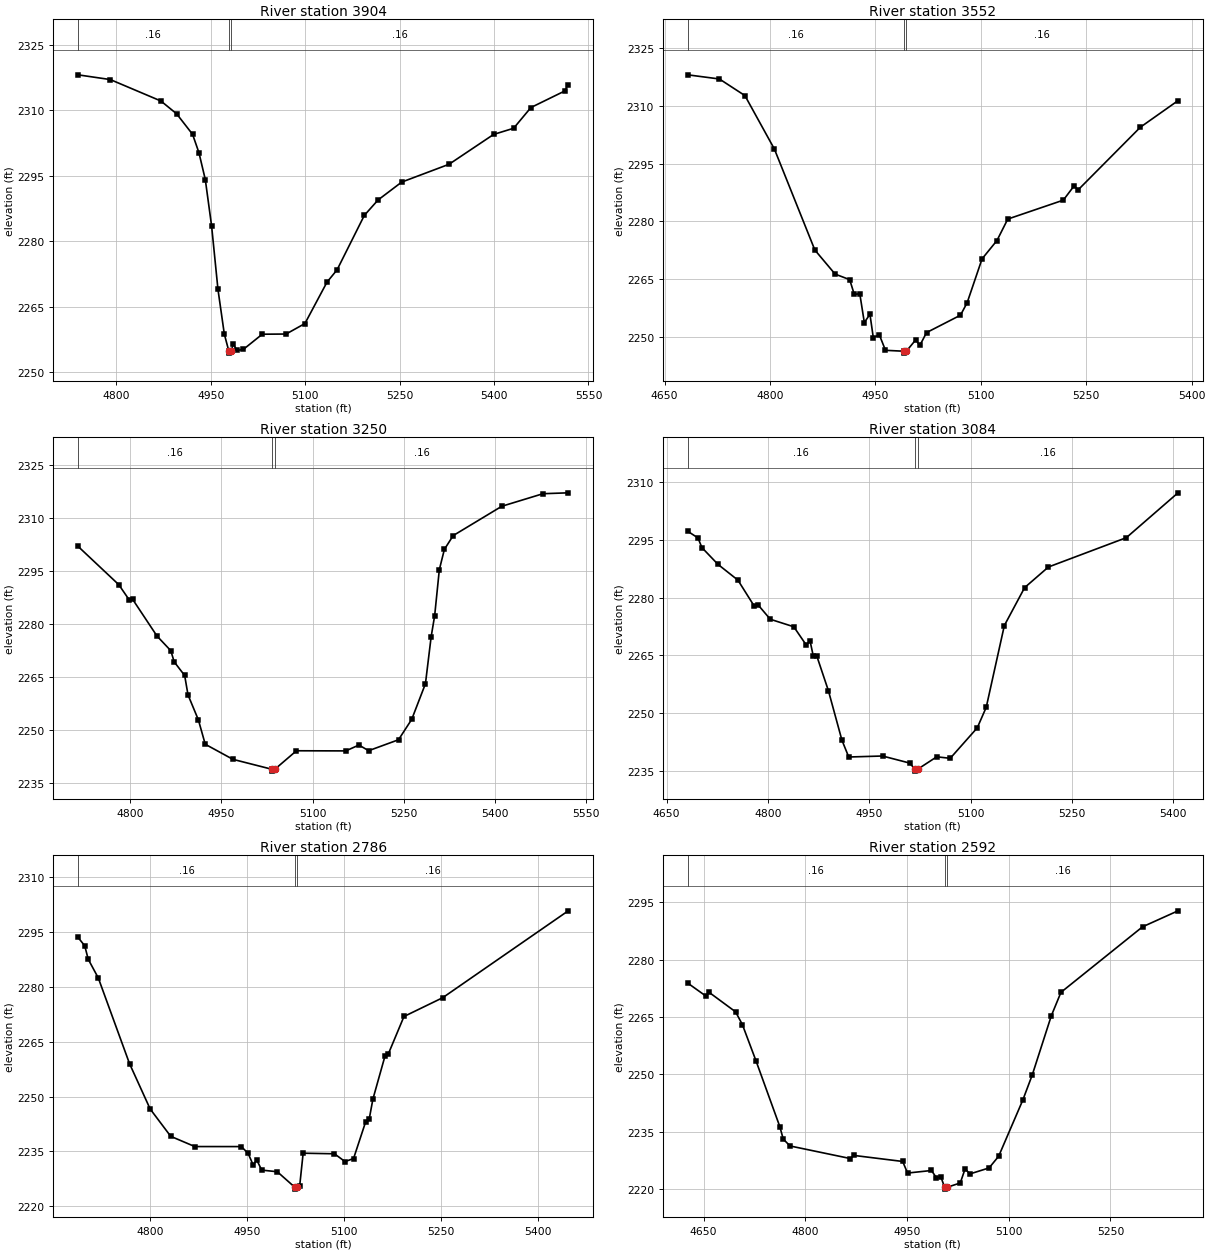
Type RM Length L Ch R = 1 ,3904    ,352,352,352
BEGIN DESCRIPTION:
elmc332
END DESCRIPTION:
XS GIS Cut Line= 3
       1505322.4      6768237.02      1505356.25      6768536.51
      1505590.26      6768952.52
#Sta/Elev= 30
  4739.1 2318.08  4790.4    2317  4870.9 2312.09  4895.9 2309.15  4921.2 2304.46
  4931.3 2300.25  4941.4 2294.11  4951.4  2283.5  4961.5 2268.98  4971.6 2258.75
  4978.7 2254.89    4979 2254.39  4982.7 2254.89  4985.7  2256.5  4991.7 2255.01
  5001.7 2255.23  5031.9 2258.72  5069.7 2258.76  5099.6 2261.16  5134.7 2270.64
  5150.7 2273.46    5194 2285.92  5215.7 2289.43  5253.3 2293.53  5328.5 2297.61
  5399.3 2304.44  5431.1 2305.85  5458.5 2310.59  5512.1 2314.37  5517.8 2315.86
#Mann= 3 ,-1 , 0
  4739.1     .16       0  4978.7     .07       0  4982.7     .16       0
Bank Sta=4978.7,4982.7
XS Rating Curve= 0 ,0
Exp/Cntr=0.3,0.1

Type RM Length L Ch R = 1 ,3552    ,302,302,302
BEGIN DESCRIPTION:
elmc331
END DESCRIPTION:
XS GIS Cut Line= 3
      1504994.25      6768554.71      1505160.94      6768760.47
       1505528.1      6768989.62
#Sta/Elev= 30
    4683 2318.09  4728.1 2317.01  4764.4 2312.69  4806.4 2298.76  4863.9 2272.52
  4892.7 2266.26  4913.5 2264.81  4919.9 2261.03  4927.9  2261.1  4934.3 2253.66
  4942.3 2255.81  4947.1 2249.68  4955.5 2250.53  4964.4 2246.43  4990.1  2246.2
  4990.4  2245.7  4994.1  2246.2  5007.4 2249.15  5013.3  2247.7  5022.8 2251.04
  5071.1 2255.57  5080.6 2258.81  5101.8 2270.22    5123 2274.99  5138.4 2280.57
  5217.4 2285.49  5232.7 2289.19  5238.6 2288.18  5327.1 2304.47  5380.6 2311.37
#Mann= 3 ,-1 , 0
    4683     .16       0  4990.1     .07       0  4994.1     .16       0
Bank Sta=4990.1,4994.1
XS Rating Curve= 0 ,0
Exp/Cntr=0.3,0.1

Type RM Length L Ch R = 1 ,3250    ,166,166,166
BEGIN DESCRIPTION:
elmc187
END DESCRIPTION:
XS GIS Cut Line= 3
      1504903.11      6768708.34       1505024.9      6768967.77
      1505277.71      6769423.78
#Sta/Elev= 30
  4713.4 2302.09  4780.8 2291.19    4798 2286.87  4803.6 2287.04  4843.7 2276.65
  4866.5 2272.49    4872 2269.34  4889.3 2265.47  4894.8 2259.98  4911.9 2252.89
  4923.2 2245.99  4968.8 2241.71  5033.7 2238.87    5034 2238.37  5037.7 2238.87
  5073.5 2244.14  5154.8  2244.1  5176.5 2245.76  5192.5 2244.16  5241.7 2247.26
  5263.5 2253.04  5286.1 2263.14  5295.5 2276.44  5301.3 2282.44    5309 2295.47
  5317.3  2301.2  5331.8 2305.11  5411.9 2313.42  5479.8 2316.98  5521.4 2317.23
#Mann= 3 ,-1 , 0
  4713.4     .16       0  5033.7     .07       0  5037.7     .16       0
Bank Sta=5033.7,5037.7
XS Rating Curve= 0 ,0
Exp/Cntr=0.3,0.1

Type RM Length L Ch R = 1 ,3084    ,298,298,298
BEGIN DESCRIPTION:
elma825
END DESCRIPTION:
XS GIS Cut Line= 4
       1504821.9      6768733.97      1504893.62       6768908.6
      1504874.91      6769253.23      1504893.52        6769444.
#Sta/Elev= 30
  4681.2 2297.23  4696.4 2295.48  4702.2 2292.98  4726.1  2288.6  4755.5 2284.52
  4779.5 2277.81  4784.9 2278.18  4803.4 2274.35  4838.2  2272.4  4856.8 2267.61
  4862.2 2268.78    4867 2264.82  4872.2 2264.82  4889.4  2255.8  4909.4 2242.94
  4919.5 2238.55  4969.5 2238.81  5009.6 2236.98  5017.6 2235.38  5017.9 2234.88
  5021.6 2235.38  5049.7  2238.6  5069.7 2238.21  5109.7 2246.13    5123 2251.47
  5149.8 2272.72  5179.8 2282.57    5215 2287.93  5330.4 2295.56  5406.8 2307.21
#Mann= 3 ,-1 , 0
  4681.2     .16       0  5017.6     .07       0  5021.6     .16       0
Bank Sta=5017.6,5021.6
XS Rating Curve= 0 ,0
Exp/Cntr=0.3,0.1

Type RM Length L Ch R = 1 ,2786    ,194,194,194
BEGIN DESCRIPTION:
elmc186
END DESCRIPTION:
XS GIS Cut Line= 3
      1504754.99      6768738.02       1504658.3      6769033.92
      1504824.98      6769447.92
#Sta/Elev= 30
  4688.7 2293.61  4699.2 2291.29  4704.6  2287.6  4720.2 2282.46  4768.4 2259.02
  4800.3 2246.59  4832.1  2239.1  4869.3  2236.3  4941.2 2236.29  4951.7 2234.43
  4959.6  2231.2  4964.9 2232.65  4972.7 2229.85  4996.8  2229.4  5023.9 2225.14
  5024.2 2224.64  5027.9 2225.14  5031.3 2225.44  5036.7 2234.48  5085.1 2234.32
  5101.4 2232.18  5114.6 2233.02  5133.4 2243.14  5138.8 2243.84  5144.5  2249.3
    5163 2260.98  5168.3 2261.65  5192.5 2271.92  5252.3 2277.06  5446.3 2300.86
#Mann= 3 ,-1 , 0
  4688.7     .16       0  5023.9     .07       0  5027.9     .16       0
Bank Sta=5023.9,5027.9
XS Rating Curve= 0 ,0
Exp/Cntr=0.3,0.1

Type RM Length L Ch R = 1 ,2592    ,248,248,248
BEGIN DESCRIPTION:
elmc330
END DESCRIPTION:
XS GIS Cut Line= 3
       1504447.4      6768817.73      1504476.04      6769125.05
       1504765.1      6769421.92
#Sta/Elev= 30
  4626.6 2273.89  4653.3 2270.51  4658.3 2271.45  4697.2 2266.37  4707.2 2263.05
  4727.3 2253.57  4762.4 2236.39  4767.5 2233.11  4777.5 2231.32  4866.5 2228.03
  4871.5 2228.85  4943.6 2227.27  4950.8 2224.24  4986.1 2224.91  4993.2 2223.04
  5000.2  2223.1  5005.4 2220.54  5005.6 2220.04  5009.4 2220.54  5028.5 2221.65
  5035.7 2225.36  5042.7 2224.01    5071 2225.58  5085.1 2228.62  5120.6 2243.25
  5134.7 2249.89  5162.8 2265.35    5177 2271.47  5297.3 2288.59  5349.6 2292.77
#Mann= 3 ,-1 , 0
  4626.6     .16       0  5005.4     .07       0  5009.4     .16       0
Bank Sta=5005.4,5009.4
XS Rating Curve= 0 ,0
Exp/Cntr=0.3,0.1

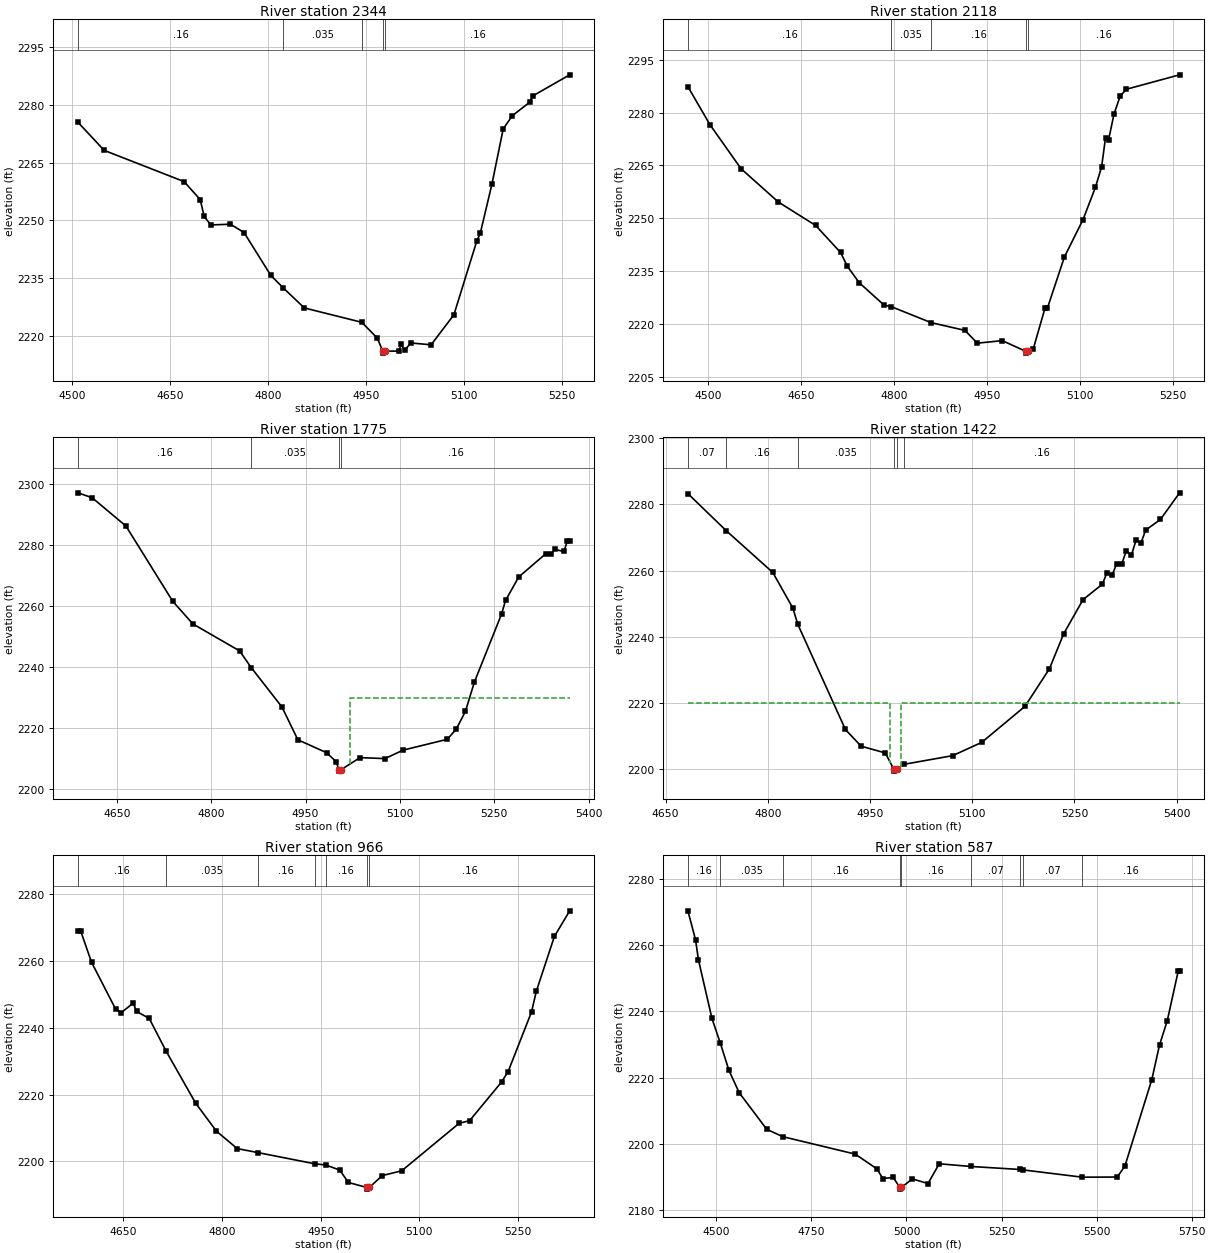
Type RM Length L Ch R = 1 ,2344    ,226,226,226
BEGIN DESCRIPTION:
elmc185
END DESCRIPTION:
XS GIS Cut Line= 3
      1503965.65      6769237.04      1504447.11      6769331.84
      1504699.97      6769398.48
#Sta/Elev= 30
  4509.3 2275.47  4549.4 2268.19  4671.7 2260.08  4696.3  2255.4  4702.3 2251.05
  4712.5 2248.84  4742.6 2249.03  4763.4 2246.86  4804.2 2235.75  4823.6 2232.45
  4855.5  2227.3  4943.4 2223.57  4967.3 2219.46  4975.5 2216.07  4975.7 2215.57
  4979.5 2216.07    5000 2216.11  5003.8 2217.89  5008.9 2216.28  5018.5 2218.21
  5049.5 2217.73  5084.4 2225.53  5119.5 2244.72  5124.7 2246.67  5142.6 2259.45
  5159.8 2273.76  5173.6 2277.16  5200.1 2280.66  5205.3 2282.35  5261.5  2287.8
#Mann= 5 ,-1 , 0
  4509.3     .16       0  4823.6    .035       0  4943.4     .16       0
  4975.5     .07       0  4979.5     .16       0
Bank Sta=4975.5,4979.5
XS Rating Curve= 0 ,0
Exp/Cntr=0.3,0.1

Type RM Length L Ch R = 1 ,2118    ,343,343,343
BEGIN DESCRIPTION:
elmc329
END DESCRIPTION:
XS GIS Cut Line= 3
      1503939.54       6769591.2      1504517.71      6769549.53
      1504730.59      6769557.32
#Sta/Elev= 30
  4467.6 2287.35  4503.2 2276.54  4553.3 2264.05  4613.4 2254.59  4673.6 2247.93
  4713.7 2240.27  4724.8 2236.32  4743.8 2231.67  4783.9 2225.32  4795.3 2224.89
  4859.7 2220.34  4914.2 2218.14  4934.3 2214.51  4974.4 2215.23  5012.5 2212.18
  5012.7 2211.68  5016.5 2212.18  5024.5 2212.92  5043.4  2224.5  5047.3  2224.5
  5074.6 2238.97  5104.6 2249.58  5124.6 2258.74  5134.6 2264.57  5140.9 2272.85
  5145.9  2272.3  5154.6 2279.58  5164.6  2284.7  5174.6 2286.62  5260.3 2290.71
#Mann= 5 ,-1 , 0
  4467.6     .16       0  4795.3    .035       0  4859.7     .16       0
  5012.5     .07       0  5016.5     .16       0
Bank Sta=5012.5,5016.5
XS Rating Curve= 0 ,0
Exp/Cntr=0.3,0.1

Type RM Length L Ch R = 1 ,1775    ,353,353,353
BEGIN DESCRIPTION:
elmc184
END DESCRIPTION:
XS GIS Cut Line= 3
       1504033.3      6769992.25      1504481.25      6769830.78
      1504718.22      6769638.08
#Sta/Elev= 30
  4588.3 2297.18  4610.8 2295.57  4664.5 2286.29  4738.9 2261.61  4770.8  2254.2
  4845.2 2245.34  4863.7 2239.85  4912.4 2226.98  4937.8 2216.19  4983.4 2211.96
  4999.2  2208.9  5002.7 2206.41  5002.9 2205.91  5006.7 2206.41  5036.6 2210.34
  5076.3 2210.02    5105 2212.79  5175.4 2216.35  5189.8 2219.76  5204.1 2225.48
  5218.5 2235.15  5261.6 2257.41    5268 2261.91  5288.9 2269.58    5332 2277.23
  5339.9 2277.01  5346.3 2278.62  5360.7 2277.95    5366 2281.26  5369.9 2281.26
#Mann= 4 ,-1 , 0
  4588.3     .16       0  4863.7    .035       0  5002.7    .035       0
  5006.7     .16       0
#XS Ineff= 2 , 0
       0                    5020       0    2230
Permanent Ineff=
       F       F
Bank Sta=5002.7,5006.7
XS Rating Curve= 0 ,0
Exp/Cntr=0.3,0.1

Type RM Length L Ch R = 1 ,1422    ,456,456,456
BEGIN DESCRIPTION:
elmc183
END DESCRIPTION:
XS GIS Cut Line= 3
      1504298.98      6770346.39      1504554.49      6770158.42
      1504855.02      6769887.98
#Sta/Elev= 30
  4682.8 2283.25  4739.1 2272.05  4807.4 2259.45  4836.7 2248.75  4844.1 2243.79
  4913.9 2212.07    4937 2207.01  4972.5 2204.98  4985.1 2199.99  4985.4 2199.49
  4989.1 2199.99  4999.5 2201.53  5071.3 2204.16  5113.9 2208.16  5177.4 2219.03
  5213.3 2230.37  5234.2 2240.93  5262.6 2251.24    5291 2255.91  5297.8 2259.41
  5305.2 2258.56    5312 2262.11  5319.4 2262.02  5326.2 2265.99  5333.6 2264.66
  5340.4 2269.15  5347.8 2268.46  5354.6 2272.26  5376.2 2275.44  5404.3 2283.49
#Mann= 6 ,-1 , 0
  4682.8     .07       0  4739.1     .16       0  4844.1    .035       0
  4985.1     .07       0  4989.1    .035       0  4999.5     .16       0
#XS Ineff= 2 , 0
       0    4980    2220    4995       0    2220
Permanent Ineff=
       F       F
Bank Sta=4985.1,4989.1
XS Rating Curve= 0 ,0
Exp/Cntr=0.3,0.1

Type RM Length L Ch R = 1 ,966     ,379,379,379
BEGIN DESCRIPTION:
elmc182
END DESCRIPTION:
XS GIS Cut Line= 3
      1504382.27      6770395.88      1504694.79      6770500.05
      1505054.98      6770288.01
#Sta/Elev= 30
    4581 2268.99  4585.1 2268.99  4601.6 2259.63  4638.5  2245.5  4647.1  2244.6
  4664.9 2247.42  4670.1 2244.91  4689.3 2242.82  4714.8 2233.07  4759.7 2217.51
  4791.3  2209.1    4823 2203.86  4854.4 2202.66  4941.1  2199.3  4957.8 2198.94
    4979 2197.41  4991.9 2193.72  5019.9 2192.22  5020.2 2191.72  5023.9 2192.22
  5043.4 2195.77  5073.1 2197.21  5160.5 2211.45  5176.2  2212.2  5224.9  2223.8
  5234.8  2226.9  5270.4 2244.76  5277.7 2250.96  5305.2 2267.38  5328.4 2275.04
#Mann= 7 ,-1 , 0
    4581     .16       0  4714.8    .035       0  4854.4     .16       0
  4941.1    .035       0  4957.8     .16       0  5019.9     .07       0
  5023.9     .16       0
Bank Sta=5019.9,5023.9
XS Rating Curve= 0 ,0
Exp/Cntr=0.3,0.1

Type RM Length L Ch R = 1 ,587     ,218,218,218
BEGIN DESCRIPTION:
elmc328
END DESCRIPTION:
XS GIS Cut Line= 4
      1504371.87      6770442.76      1504817.19      6770731.82
      1505056.77      6770789.11      1505567.17       6770713.6
#Sta/Elev= 30
  4425.1 2270.37  4445.3 2261.56  4452.7 2255.65  4488.4 2237.84  4510.5 2230.35
    4533 2222.19    4560 2215.42  4632.5 2204.37  4674.7 2202.14  4865.2 2196.87
  4922.5 2192.39  4937.7  2189.5  4965.1 2189.81  4982.6 2186.79  4982.9 2186.29
  4986.6 2186.79  5015.4 2189.38  5056.6 2187.98  5086.2 2193.95  5168.5 2193.14
  5299.5 2192.22  5305.2 2192.12  5462.3  2189.9  5554.4 2189.94  5574.6 2193.29
  5645.3 2219.39  5665.6 2229.86  5685.8 2237.12  5714.7 2252.14  5718.3 2252.14
#Mann= 9 ,-1 , 0
  4425.1     .16       0  4510.5    .035       0  4674.7     .16       0
  4982.6     .07       0  4986.6     .16       0  5168.5     .07       0
  5299.5     .16       0  5305.2     .07       0  5462.3     .16       0
Bank Sta=4982.6,4986.6
XS Rating Curve= 0 ,0
Exp/Cntr=0.3,0.1

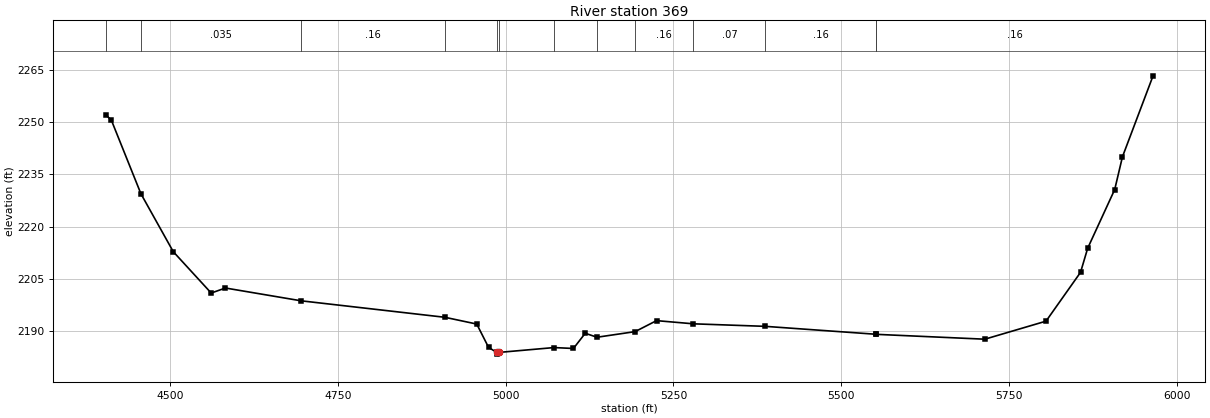
Type RM Length L Ch R = 1 ,369     ,0,0,0
BEGIN DESCRIPTION:
elmc327
END DESCRIPTION:
XS GIS Cut Line= 4
      1504327.63       6770513.1      1504702.61      6770898.49
      1504897.92      6770987.03      1505691.06       6770833.6
#Sta/Elev= 30
  4404.3 2252.17  4412.9 2250.52  4456.8 2229.48    4505 2212.87  4561.5 2201.02
  4582.7 2202.46  4695.5 2198.79  4909.5 2194.07    4957 2192.13  4974.6 2185.45
  4986.6 2184.01  4986.8 2183.51  4990.6 2184.01  5072.1 2185.39    5101 2185.13
  5118.6 2189.49  5136.1 2188.35  5192.9 2189.96  5224.8 2193.11  5279.5  2192.2
  5386.9 2191.47  5551.2 2189.21  5552.3 2189.18  5713.7 2187.79  5804.9 2192.96
  5856.3 2206.95  5866.9 2213.84  5907.2 2230.69  5918.7 2240.05  5964.3 2263.28
#Mann= 13 ,-1 , 0
  4404.3     .16       0  4456.8    .035       0  4695.5     .16       0
  4909.5    .035       0  4986.6    .035       0  4990.6    .035       0
  5072.1     .16       0  5136.1    .035       0  5192.9     .16       0
  5279.5     .07       0  5386.9     .16       0  5551.2     .07       0
  5552.3     .16       0
Bank Sta=4986.6,4990.6
XS Rating Curve= 0 ,0
Exp/Cntr=0.3,0.1

Chan Stop Cuts=-1
Use User Specified Reach Order=0
Composite Channel Slope=5