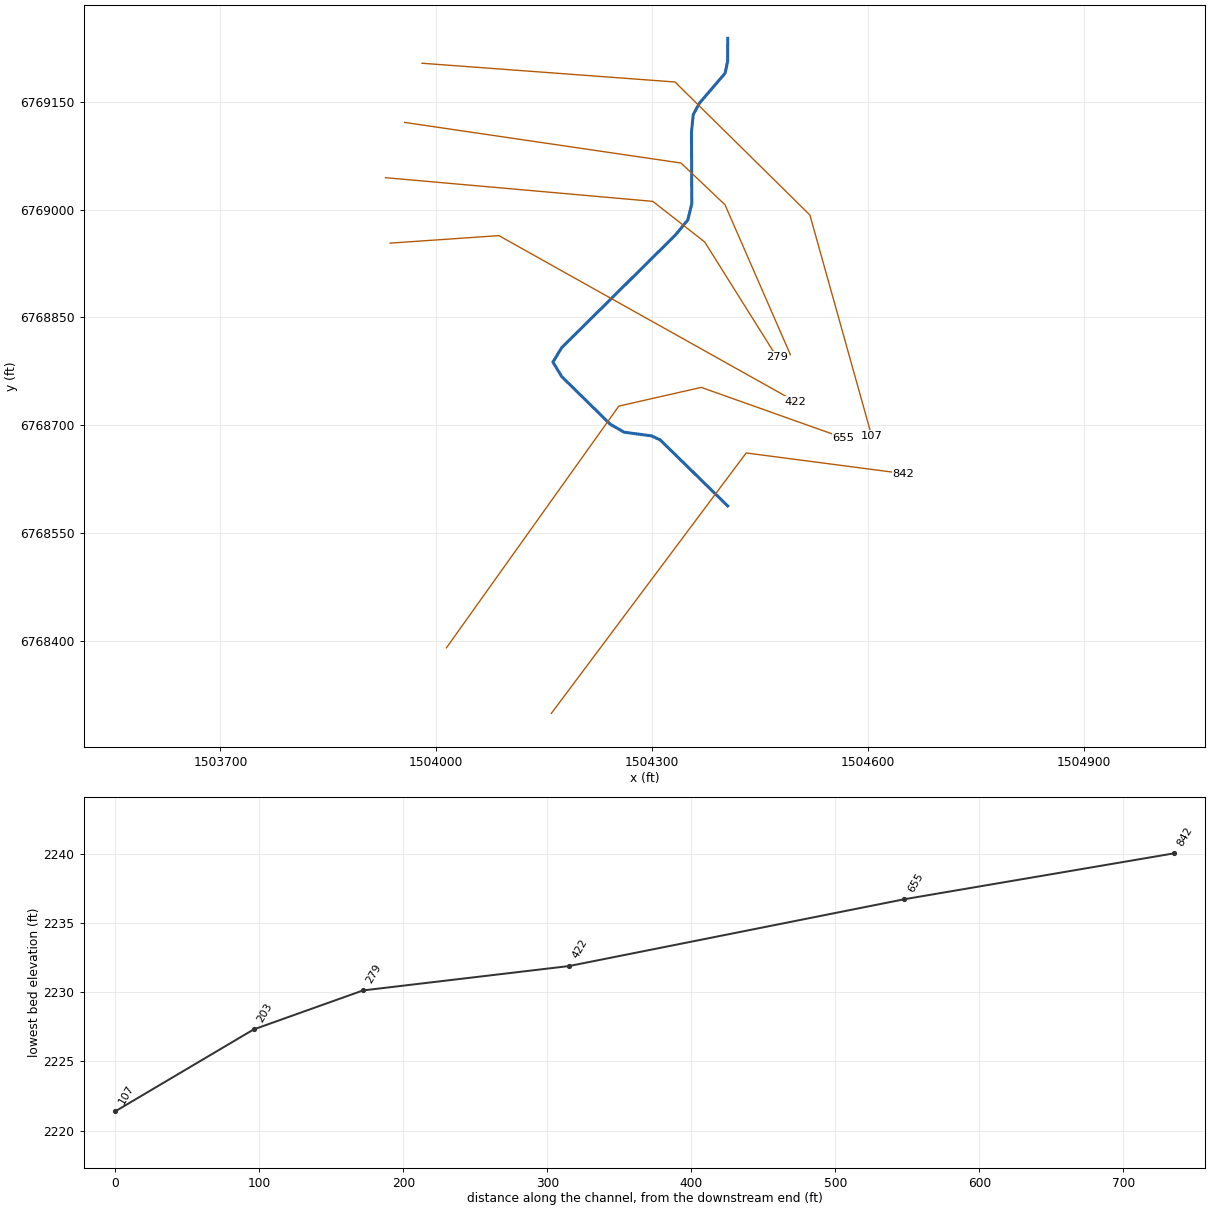
--- Elm 41.prj (project) ---

Proj Title=Elm 41 Base Level Engineering
Current Plan=p01
Default Exp/Contr=0.3,0.1
English Units
Geom File=g01
Flow File=f01
Plan File=p01
BEGIN DESCRIPTION:
Elm 41
END DESCRIPTION:

--- Elm 41.p01 (plan) ---

Plan Title=Multiple Run
Short Identifier=Multiple
Geom File=g01
Flow File=f01
Subcritical Flow
K Sum by GR= 0
Std Step Tol= 0.01
Critical Tol= 0.01
Num of Std Step Trials= 20
Max Error Tol= 0.3
Flow Tol Ratio= 0.001
Split Flow NTrial= 30
Split Flow Tol= 0.02
Split Flow Ratio= 0.02
Log Output Level= 0
Friction Slope Method= 1
Unsteady Friction Slope Method= 2
Unsteady Bridges Friction Slope Method= 1
Parabolic Critical Depth
Global Vel Dist=  1 , 1 , 1
Global Log Level= 0
CheckData=True
Encroach Param= -1, 0, 0, 0
BEGIN DESCRIPTION:
Multiple Run
END DESCRIPTION:

--- Elm 41.f01 (steady flow) ---

Flow Title=Multiple
Number of Profiles=7
Profile Names=10-year,25-year,50-year,1pct_min,100-year,1pct_plu,500-year
River Rch & RM= Elm 41,Reach-1,842
     156     214     261     199     319     439     480
Boundary for River Rch & Prof#=Elm 41,Reach-1,1
Up Type=0
Dn Type=3
Dn Slope=0.005
Boundary for River Rch & Prof#=Elm 41,Reach-1,2
Up Type=0
Dn Type=3
Dn Slope=0.005
Boundary for River Rch & Prof#=Elm 41,Reach-1,3
Up Type=0
Dn Type=3
Dn Slope=0.005
Boundary for River Rch & Prof#=Elm 41,Reach-1,4
Up Type=0
Dn Type=3
Dn Slope=0.005
Boundary for River Rch & Prof#=Elm 41,Reach-1,5
Up Type=0
Dn Type=3
Dn Slope=0.005
Boundary for River Rch & Prof#=Elm 41,Reach-1,6
Up Type=0
Dn Type=3
Dn Slope=0.005
Boundary for River Rch & Prof#=Elm 41,Reach-1,7
Up Type=0
Dn Type=3
Dn Slope=0.005

--- Elm 41.g01 (geometry) ---

Geom Title=Existing Conditions

River Reach=Elm 41,Reach-1
Reach XY= 21
      1504405.00      6768588.00      1504358.03      6768633.95
      1504311.07      6768679.89      1504298.95      6768685.48
      1504261.02      6768690.52      1504241.73      6768701.63
      1504174.19      6768767.96      1504162.07      6768787.99
      1504174.21      6768808.00      1504226.85      6768860.15
      1504279.50      6768912.31      1504332.14      6768964.47
      1504349.53      6768985.55      1504355.02      6769007.99
      1504354.84      6769058.07      1504354.66      6769108.14
      1504357.14      6769132.12      1504365.57      6769147.76
      1504401.35      6769189.51      1504404.88      6769206.20
      1504405.00      6769238.00

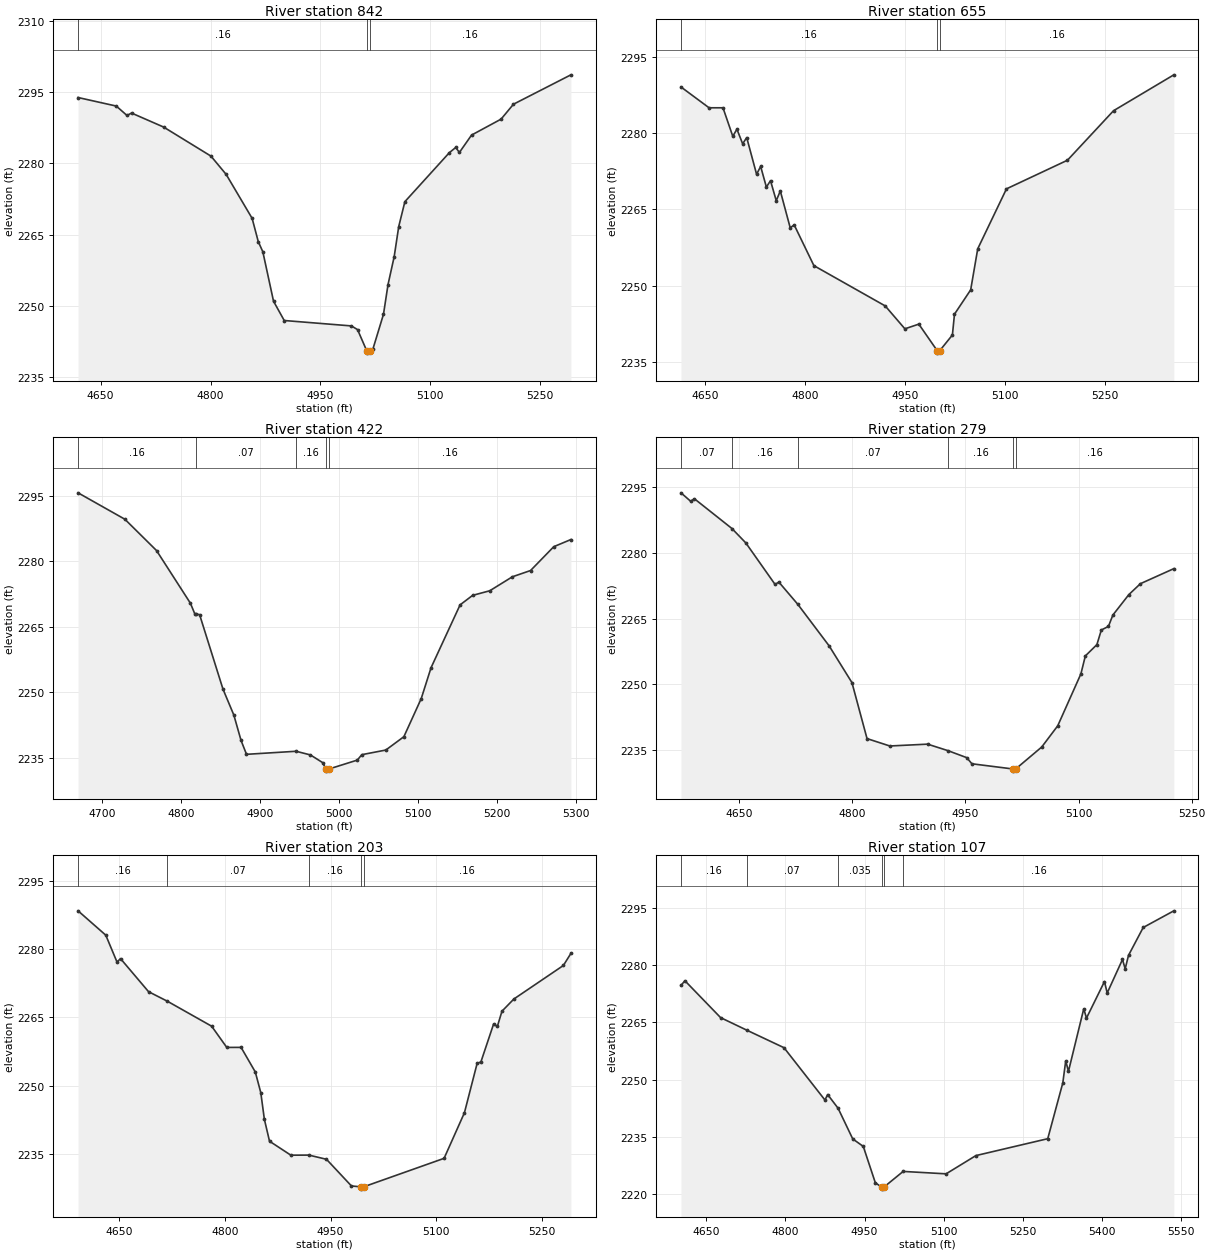
Type RM Length L Ch R = 1,842,187,187,187
BEGIN DESCRIPTION:
elmc335
END DESCRIPTION:
XS GIS Cut Line= 3
      1504159.85      6768299.74      1504430.67      6768661.70
      1504649.45      6768633.05
#Sta/Elev= 30
  4619.2 2293.86  4671.4 2292.06  4686.0 2290.08  4692.2 2290.59  4736.0 2287.64
  4800.6 2281.52  4821.4 2277.66  4856.8 2268.41  4865.2 2263.50  4871.4 2261.38
  4886.0 2250.96  4900.6 2246.90  4992.3 2245.76  5000.7 2244.98  5013.2 2240.53
  5013.5 2240.03  5017.2 2240.53  5021.5 2240.81  5036.1 2248.22  5042.3 2254.48
  5050.7 2260.35  5056.9 2266.69  5065.3 2271.93  5126.0 2282.25  5134.7 2283.34
  5139.7 2282.29  5156.3 2285.95  5196.6 2289.31  5213.5 2292.45  5291.9 2298.64
#Mann=3,-1,0
  4619.2    0.16       0  5013.2    0.07       0  5017.2    0.16       0
Bank Sta=5013.2,5017.2
Exp/Cntr=0.3,0.1

Type RM Length L Ch R = 1,655,233,233,233
BEGIN DESCRIPTION:
elmc334
END DESCRIPTION:
XS GIS Cut Line= 4
      1504014.02      6768390.88      1504253.59      6768726.80
      1504368.17      6768752.84      1504565.39      6768682.78
#Sta/Elev= 30
  4614.0 2289.05  4656.1 2284.96  4677.0 2284.96  4691.7 2279.35  4697.9 2280.75
  4706.5 2277.88  4712.6 2279.10  4727.4 2271.89  4733.5 2273.43  4742.1 2269.37
  4748.3 2270.63  4756.9 2266.69  4763.0 2268.61  4777.8 2261.39  4783.9 2261.91
  4813.4 2253.92  4920.4 2246.00  4949.9 2241.50  4970.8 2242.42  4998.3 2237.22
  4998.5 2236.72  5002.3 2237.22  5021.2 2240.29  5024.3 2244.38  5048.6 2249.16
  5059.2 2257.24  5102.3 2269.02  5193.8 2274.65  5262.9 2284.38  5353.4 2291.44
#Mann=3,-1,0
  4614.0    0.16       0  4998.3    0.07       0  5002.3    0.16       0
Bank Sta=4998.3,5002.3
Exp/Cntr=0.3,0.1

Type RM Length L Ch R = 1,422,143,143,143
BEGIN DESCRIPTION:
elmc210
END DESCRIPTION:
XS GIS Cut Line= 3
      1503935.84      6768953.36      1504086.92      6768963.78
      1504499.63      6768732.77
#Sta/Elev= 30
  4669.5 2295.65  4728.8 2289.60  4768.9 2282.43  4811.8 2270.37  4817.5 2267.88
  4819.5 2267.88  4823.5 2267.73  4853.1 2250.68  4866.9 2244.72  4876.0 2238.92
  4882.9 2235.74  4945.7 2236.44  4963.9 2235.60  4979.2 2233.86  4983.6 2232.39
  4983.9 2231.89  4987.6 2232.39  5023.3 2234.42  5029.0 2235.66  5059.4 2236.72
  5082.3 2239.78  5104.3 2248.52  5116.7 2255.58  5153.5 2269.98  5169.4 2272.16
  5191.1 2273.21  5219.8 2276.42  5242.8 2277.85  5272.2 2283.31  5293.9 2284.95
#Mann=5,-1,0
  4669.5    0.16       0  4819.5    0.07       0  4945.7    0.16       0
  4983.6    0.07       0  4987.6    0.16       0
Bank Sta=4983.6,4987.6
Exp/Cntr=0.3,0.1

Type RM Length L Ch R = 1,279,76,76,76
BEGIN DESCRIPTION:
elma824
END DESCRIPTION:
XS GIS Cut Line= 4
      1503929.33      6769044.32      1504300.86      6769011.40
      1504372.98      6768954.96      1504473.29      6768795.09
#Sta/Elev= 30
  4573.0 2293.78  4585.8 2291.85  4590.8 2292.42  4640.5 2285.62  4659.0 2282.31
  4697.7 2272.83  4702.7 2273.37  4727.9 2268.27  4769.4 2258.77  4799.6 2250.38
  4819.6 2237.57  4849.8 2235.88  4899.9 2236.30  4927.1 2234.80  4951.8 2233.21
  4958.6 2231.81  5012.7 2230.63  5013.0 2230.13  5016.7 2230.63  5051.2 2235.65
  5072.4 2240.50  5103.1 2252.37  5109.0 2256.48  5124.3 2259.06  5130.2 2262.41
  5139.6 2263.23  5145.5 2265.83  5166.7 2270.51  5182.0 2273.00  5226.3 2276.44
#Mann=6,-1,0
  4573.0    0.07       0  4640.5    0.16       0  4727.9    0.07       0
  4927.1    0.16       0  5012.7    0.07       0  5016.7    0.16       0
Bank Sta=5012.7,5016.7
Exp/Cntr=0.3,0.1

Type RM Length L Ch R = 1,203,96,96,96
BEGIN DESCRIPTION:
elma823
END DESCRIPTION:
XS GIS Cut Line= 4
      1503956.00      6769121.13      1504340.06      6769064.70
      1504401.20      6769006.70      1504492.11      6768798.22
#Sta/Elev= 30
  4591.4 2288.41  4630.8 2283.06  4646.7 2277.17  4651.7 2277.92  4691.5 2270.66
  4718.4 2268.55  4781.1 2263.08  4802.6 2258.42  4822.9 2258.43  4843.1 2253.03
  4850.9 2248.49  4856.0 2242.63  4863.3 2237.83  4893.6 2234.76  4919.2 2234.78
  4944.2 2233.86  4979.6 2228.01  4992.9 2227.81  4993.2 2227.31  4996.9 2227.81
  5111.2 2234.07  5140.1 2244.08  5158.1 2254.90  5163.5 2255.24  5181.5 2263.55
  5186.9 2263.05  5193.4 2266.37  5210.3 2269.05  5280.6 2276.41  5291.3 2279.06
#Mann=5,-1,0
  4591.4    0.16       0  4718.4    0.07       0  4919.2    0.16       0
  4992.9    0.07       0  4996.9    0.16       0
Bank Sta=4992.9,4996.9
Exp/Cntr=0.3,0.1

Type RM Length L Ch R = 1,107,0,0,0
BEGIN DESCRIPTION:
elmc333
END DESCRIPTION:
XS GIS Cut Line= 4
      1503980.14      6769203.37      1504331.71      6769177.32
      1504519.21      6768992.43      1504605.13      6768685.18
#Sta/Elev= 30
  4601.8 2274.67  4609.2 2275.91  4676.9 2266.26  4726.1 2263.01  4797.2 2258.39
  4874.9 2244.70  4880.0 2246.14  4899.8 2242.55  4927.6 2234.53  4947.6 2232.57
  4970.4 2223.08  4982.5 2221.90  4982.8 2221.40  4986.5 2221.90  5023.2 2226.03
  5104.7 2225.40  5161.2 2230.17  5297.5 2234.59  5326.1 2249.20  5331.6 2254.95
  5336.8 2252.21  5365.8 2268.56  5371.0 2266.14  5405.1 2275.69  5410.3 2272.70
  5439.3 2281.47  5444.4 2279.02  5450.7 2282.54  5478.6 2289.83  5536.7 2294.19
#Mann=6,-1,0
  4601.8    0.16       0  4726.1    0.07       0  4899.8   0.035       0
  4982.5   0.035       0  4986.5   0.035       0  5023.2    0.16       0
Bank Sta=4982.5,4986.5
Exp/Cntr=0.3,0.1

Chan Stop Cuts=-1