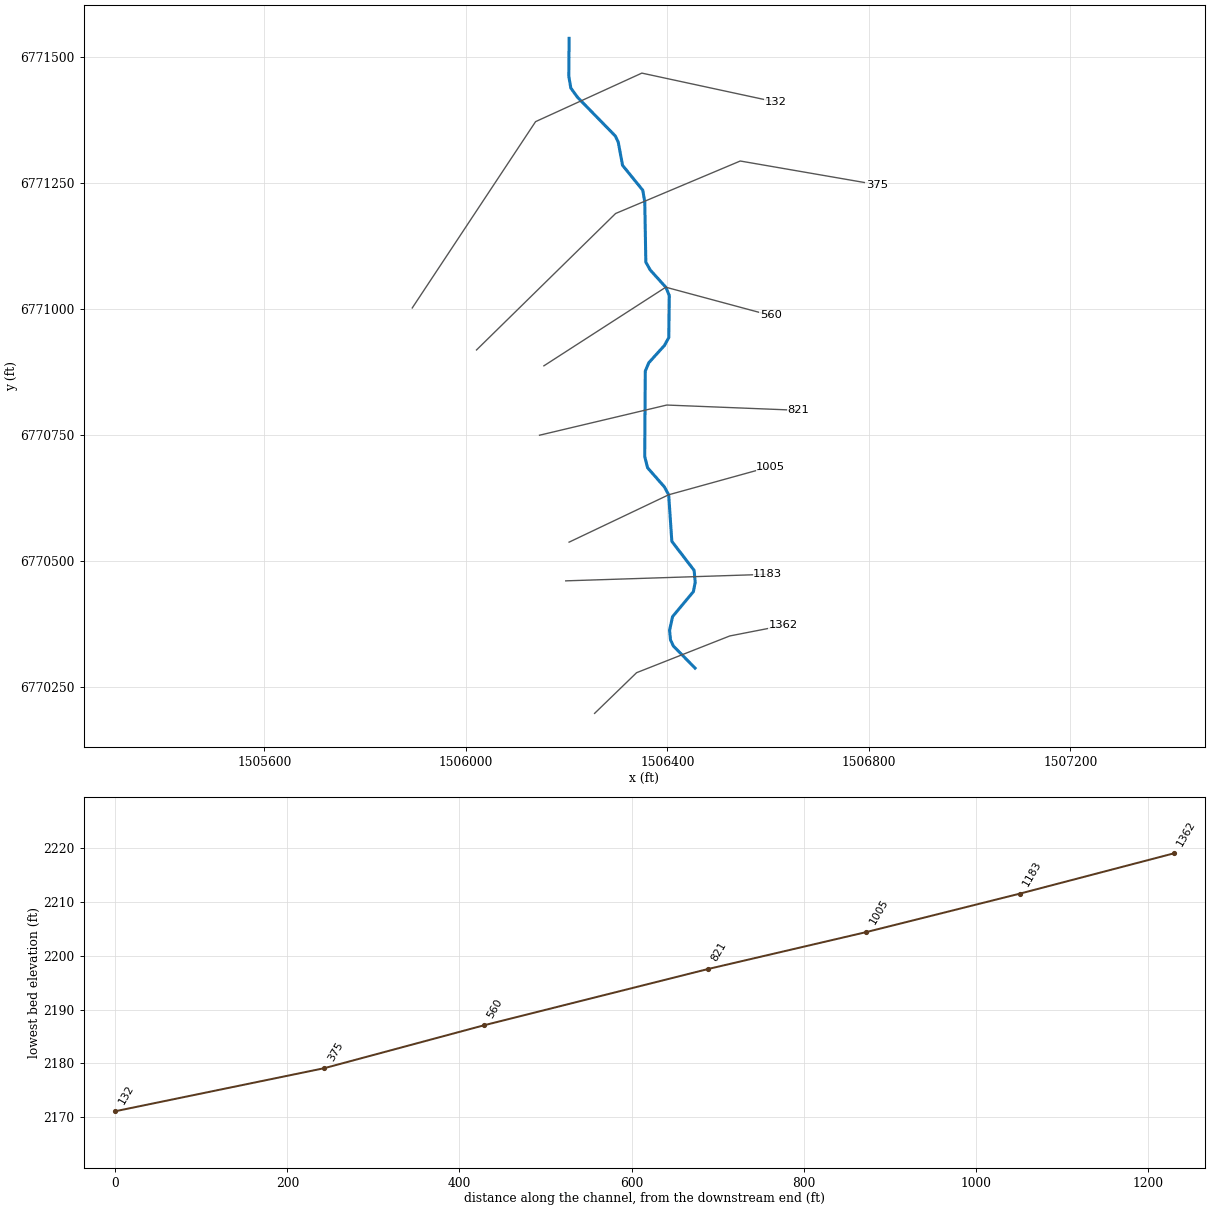
--- Elm 42.prj (project) ---

Proj Title=Elm 42 Base Level Engineering
Current Plan=p01
Default Exp/Contr=0.3,0.1
English Units
Geom File=g01
Flow File=f01
Plan File=p01
BEGIN DESCRIPTION:
Elm 42
END DESCRIPTION:

--- Elm 42.p01 (plan) ---

Plan Title=Multiple Run
Short Identifier=Multiple
Geom File=g01
Flow File=f01
Subcritical Flow
K Sum by GR= 0
Std Step Tol= 0.01
Critical Tol= 0.01
Num of Std Step Trials= 20
Max Error Tol= 0.3
Flow Tol Ratio= 0.001
Split Flow NTrial= 30
Split Flow Tol= 0.02
Split Flow Ratio= 0.02
Log Output Level= 0
Friction Slope Method= 1
Unsteady Friction Slope Method= 2
Unsteady Bridges Friction Slope Method= 1
Parabolic Critical Depth
Global Vel Dist=  1 , 1 , 1
Global Log Level= 0
CheckData=True
Encroach Param= -1, 0, 0, 0
BEGIN DESCRIPTION:
Multiple Run
END DESCRIPTION:

--- Elm 42.f01 (steady flow) ---

Flow Title=Multiple
Number of Profiles=7
Profile Names=10-year,25-year,50-year,1pct_min,100-year,1pct_plu,500-year
River Rch & RM= Elm 42,Reach-1,1362
     113     152     183     139     222     305     328
Boundary for River Rch & Prof#=Elm 42,Reach-1,1
Up Type=0
Dn Type=3
Dn Slope=0.005
Boundary for River Rch & Prof#=Elm 42,Reach-1,2
Up Type=0
Dn Type=3
Dn Slope=0.005
Boundary for River Rch & Prof#=Elm 42,Reach-1,3
Up Type=0
Dn Type=3
Dn Slope=0.005
Boundary for River Rch & Prof#=Elm 42,Reach-1,4
Up Type=0
Dn Type=3
Dn Slope=0.005
Boundary for River Rch & Prof#=Elm 42,Reach-1,5
Up Type=0
Dn Type=3
Dn Slope=0.005
Boundary for River Rch & Prof#=Elm 42,Reach-1,6
Up Type=0
Dn Type=3
Dn Slope=0.005
Boundary for River Rch & Prof#=Elm 42,Reach-1,7
Up Type=0
Dn Type=3
Dn Slope=0.005

--- Elm 42.g01 (geometry) ---

Geom Title=Existing Conditions

River Reach=Elm 42,Reach-1
Reach XY= 30
      1506455.00      6770288.00      1506411.95      6770331.85
      1506406.28      6770344.04      1506404.40      6770363.06
      1506410.41      6770390.23      1506451.62      6770439.72
      1506455.28      6770458.17      1506453.18      6770481.88
      1506408.89      6770539.58      1506402.65      6770632.02
      1506394.11      6770647.63      1506360.74      6770685.66
      1506355.07      6770708.03      1506356.22      6770877.50
      1506363.15      6770894.06      1506394.19      6770928.37
      1506402.83      6770943.98      1506403.90      6771027.45
      1506396.91      6771044.03      1506365.86      6771078.35
      1506357.27      6771093.94      1506355.19      6771213.08
      1506351.24      6771236.44      1506311.14      6771285.83
      1506302.50      6771331.96      1506296.84      6771344.05
      1506221.47      6771421.25      1506208.39      6771439.41
      1506204.41      6771462.76      1506205.00      6771538.00

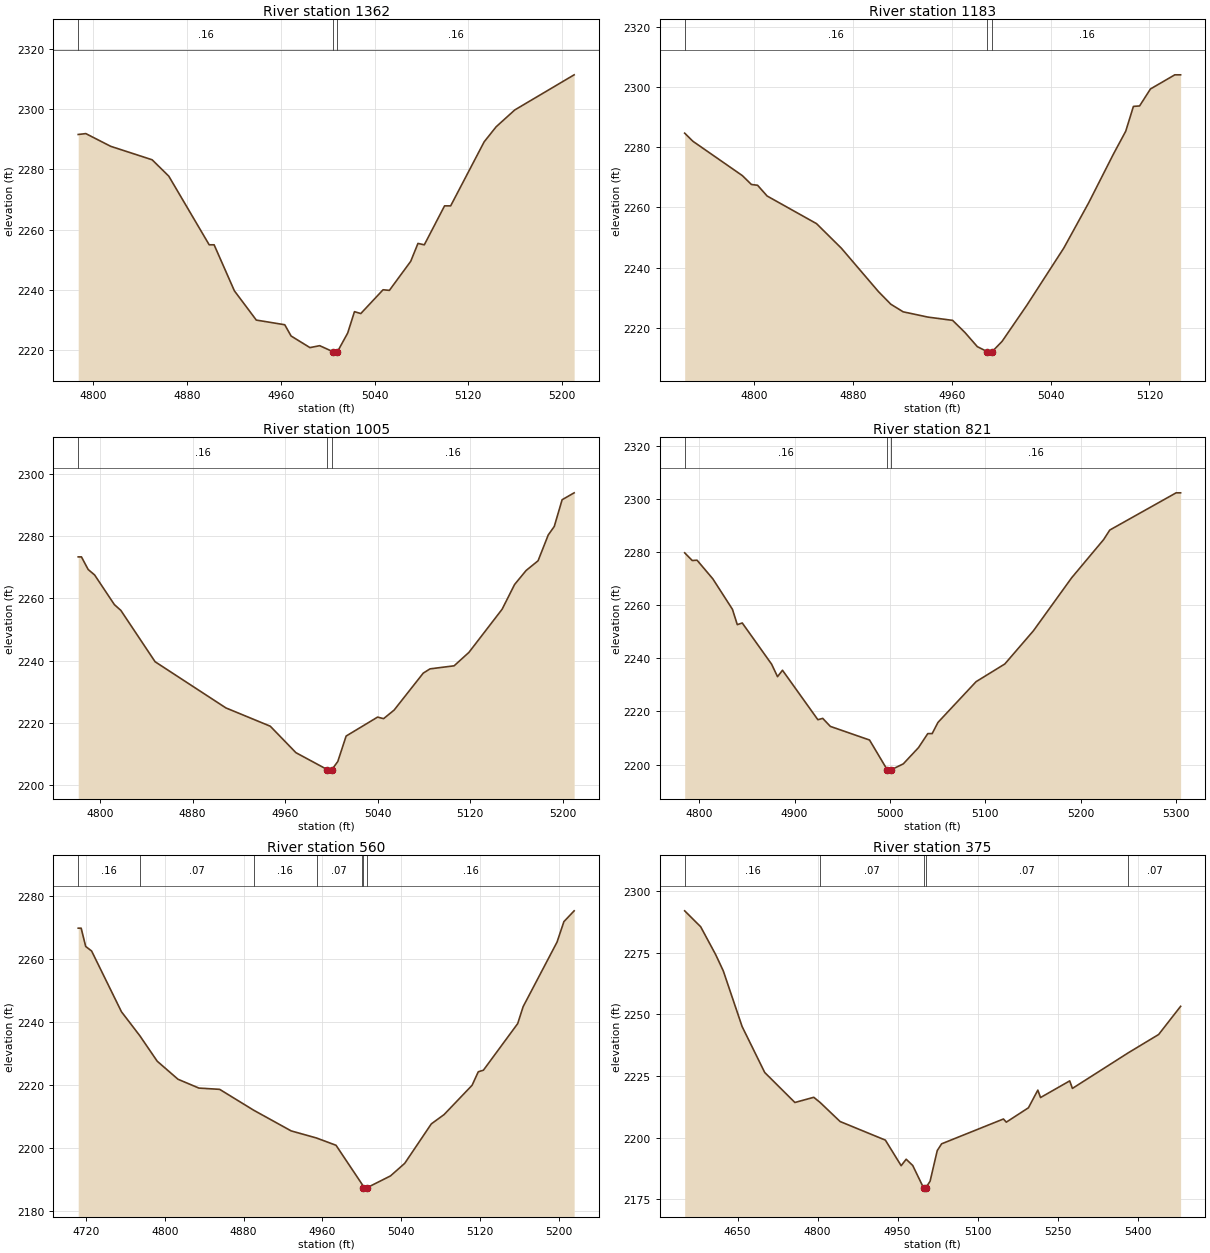
Type RM Length L Ch R = 1,1362,179,179,179
BEGIN DESCRIPTION:
elmc340
END DESCRIPTION:
XS GIS Cut Line= 4
      1506255.61      6770198.14      1506338.96      6770278.89
      1506523.85      6770351.80      1506630.35      6770372.58
#Sta/Elev= 30
  4787.1 2291.56  4793.6 2291.85  4814.8 2287.64  4850.2 2283.17  4864.4 2277.75
  4898.9 2254.98  4903.1 2254.98  4920.4 2239.72  4939.1 2230.02  4963.4 2228.47
  4968.8 2224.74  4984.9 2220.89  4993.2 2221.53  5004.4 2219.56  5004.6 2219.06
  5008.4 2219.56  5017.1 2225.71  5022.9 2232.81  5028.3 2232.18  5047.3 2240.07
  5052.7 2239.87  5070.9 2249.50  5077.1 2255.44  5082.5 2254.97  5099.8 2267.89
  5105.0 2267.89  5133.6 2289.13  5143.8 2294.10  5159.7 2299.69  5210.4 2311.34
#Mann=3,-1,0
  4787.1    0.16       0  5004.4    0.07       0  5008.4    0.16       0
Bank Sta=5004.4,5008.4
Exp/Cntr=0.3,0.1

Type RM Length L Ch R = 1,1183,178,178,178
BEGIN DESCRIPTION:
elmc339
END DESCRIPTION:
XS GIS Cut Line= 2
      1506198.31      6770461.18      1506599.40      6770474.20
#Sta/Elev= 30
  4743.9 2284.68  4750.6 2281.97  4790.6 2270.56  4797.9 2267.62  4802.9 2267.36
  4810.6 2263.79  4850.6 2254.60  4870.7 2246.43  4900.7 2232.01  4910.7 2227.82
  4920.7 2225.29  4940.7 2223.54  4960.7 2222.45  4970.7 2218.42  4980.7 2213.71
  4988.7 2212.06  4989.0 2211.56  4992.5 2211.56  4992.7 2212.06  5000.7 2215.45
  5020.7 2227.43  5050.7 2246.50  5070.8 2261.53  5090.8 2277.70  5100.8 2285.33
  5107.0 2293.57  5112.0 2293.73  5120.8 2299.37  5140.5 2304.07  5145.2 2304.07
#Mann=3,-1,0
  4743.9    0.16       0  4988.7    0.07       0  4992.7    0.16       0
Bank Sta=4988.7,4992.7
Exp/Cntr=0.3,0.1

Type RM Length L Ch R = 1,1005,184,184,184
BEGIN DESCRIPTION:
elmc217
END DESCRIPTION:
XS GIS Cut Line= 3
      1506204.97      6770537.99      1506402.65      6770632.02
      1506605.04      6770688.01
#Sta/Elev= 30
  4781.1 2273.34  4783.9 2273.34  4789.7 2269.29  4795.3 2267.53  4812.4 2257.98
  4818.0 2256.12  4847.6 2239.61  4908.8 2224.76  4947.2 2218.87  4969.4 2210.35
  4996.5 2204.92  4996.8 2204.42  5000.5 2204.92  5005.6 2207.52  5012.8 2215.70
  5040.0 2221.80  5045.2 2221.30  5054.3 2224.06  5079.5 2235.95  5085.4 2237.32
  5106.2 2238.30  5119.0 2242.62  5147.7 2256.50  5158.5 2264.46  5168.5 2268.98
  5178.8 2272.09  5187.6 2280.40  5192.8 2283.13  5199.6 2291.73  5210.0 2293.95
#Mann=3,-1,0
  4781.1    0.16       0  4996.5    0.07       0  5000.5    0.16       0
Bank Sta=4996.5,5000.5
Exp/Cntr=0.3,0.1

Type RM Length L Ch R = 1,821,261,261,261
BEGIN DESCRIPTION:
elmc338
END DESCRIPTION:
XS GIS Cut Line= 3
      1506146.30      6770750.25      1506398.85      6770810.14
      1506659.29      6770799.72
#Sta/Elev= 30
  4784.8 2279.73  4792.7 2276.84  4797.8 2276.95  4814.3 2269.95  4834.9 2258.47
  4840.0 2252.69  4845.2 2253.32  4876.0 2237.80  4882.2 2233.10  4887.4 2235.52
  4924.5 2216.90  4929.6 2217.40  4937.6 2214.38  4978.7 2209.25  4997.3 2198.04
  4997.5 2197.54  5001.3 2198.04  5014.1 2200.27  5030.1 2206.41  5039.8 2211.67
  5044.4 2211.67  5050.5 2215.89  5090.5 2231.23  5120.6 2237.88  5150.6 2250.38
  5190.6 2270.28  5224.3 2284.74  5230.7 2288.31  5300.3 2302.32  5305.0 2302.32
#Mann=3,-1,0
  4784.8    0.16       0  4997.3    0.07       0  5001.3    0.16       0
Bank Sta=4997.3,5001.3
Exp/Cntr=0.3,0.1

Type RM Length L Ch R = 1,560,185,185,185
BEGIN DESCRIPTION:
elmc216
END DESCRIPTION:
XS GIS Cut Line= 3
      1506154.97      6770887.98      1506396.91      6771044.03
      1506605.00      6770988.00
#Sta/Elev= 30
  4712.1 2269.93  4715.1 2269.93  4719.7 2264.12  4725.7 2262.68  4756.0 2243.38
  4774.6 2235.78  4792.3 2227.67  4813.4 2221.94  4834.6 2219.14  4855.7 2218.73
  4890.3 2212.09  4928.3 2205.53  4954.0 2203.28  4973.8 2200.97  5000.2 2188.60
  5001.6 2187.54  5001.8 2187.04  5005.6 2187.54  5029.1 2191.24  5043.5 2195.22
  5070.5 2207.76  5083.5 2210.73  5111.9 2220.03  5118.2 2224.32  5123.4 2224.82
  5158.2 2239.62  5163.7 2244.99  5198.1 2265.49  5205.1 2272.01  5215.5 2275.44
#Mann=7,-1,0
  4712.1    0.16       0  4774.6    0.07       0  4890.3    0.16       0
  4954.0    0.07       0  5000.2    0.16       0  5001.6    0.07       0
  5005.6    0.16       0
Bank Sta=5001.6,5005.6
Exp/Cntr=0.3,0.1

Type RM Length L Ch R = 1,375,243,243,243
BEGIN DESCRIPTION:
elmc337
END DESCRIPTION:
XS GIS Cut Line= 4
      1506021.22      6770919.48      1506297.29      6771190.34
      1506544.69      6771294.51      1506815.57      6771247.63
#Sta/Elev= 30
  4550.7 2292.09  4580.7 2285.62  4608.9 2274.28  4623.1 2267.71  4658.4 2245.11
  4700.8 2226.45  4757.4 2214.26  4792.8 2216.37  4804.7 2214.27  4842.2 2206.53
  4927.1 2198.98  4956.7 2188.60  4966.1 2191.22  4978.4 2188.68  4998.7 2179.58
  4998.9 2179.08  5002.7 2179.58  5010.9 2182.26  5024.4 2194.75  5032.6 2197.48
  5148.5 2207.56  5153.9 2206.28  5195.4 2212.11  5213.0 2219.28  5218.1 2216.27
  5272.8 2223.03  5277.9 2219.98  5382.9 2234.47  5439.6 2241.87  5480.8 2253.31
#Mann=5,-1,0
  4550.7    0.16       0  4804.7    0.07       0  4998.7    0.07       0
  5002.7    0.07       0  5382.9    0.07       0
Bank Sta=4998.7,5002.7
Exp/Cntr=0.3,0.1

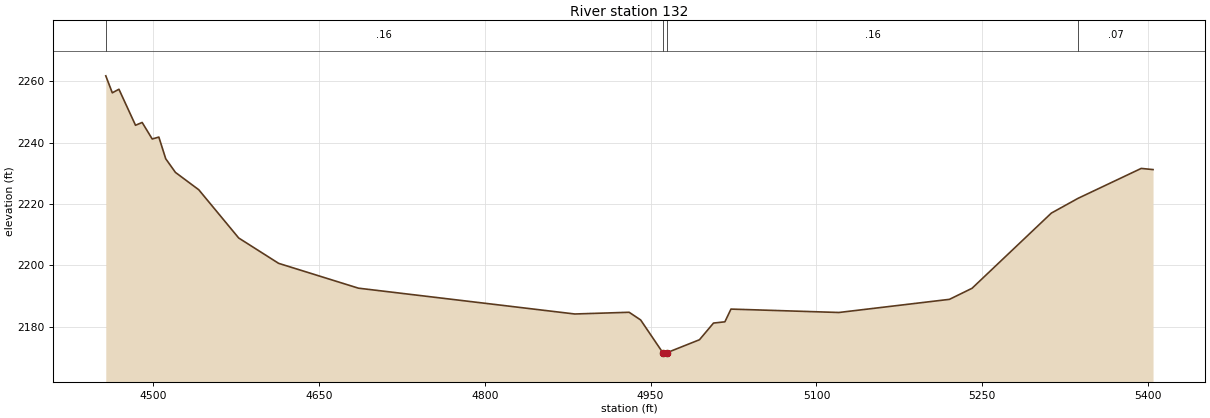
Type RM Length L Ch R = 1,132,0,0,0
BEGIN DESCRIPTION:
elmc336
END DESCRIPTION:
XS GIS Cut Line= 4
      1505893.64      6771002.83      1506138.44      6771372.64
      1506349.38      6771468.99      1506614.98      6771411.70
#Sta/Elev= 30
  4457.3 2261.83  4463.2 2256.29  4469.2 2257.45  4484.2 2245.70  4490.2 2246.62
  4499.3 2241.23  4505.3 2241.85  4511.5 2234.79  4520.3 2230.33  4541.4 2224.67
  4577.5 2208.94  4613.6 2200.67  4685.8 2192.57  4881.4 2184.15  4930.6 2184.71
  4941.0 2182.21  4961.0 2171.56  4961.2 2171.06  4965.0 2171.56  4994.2 2175.75
  5006.9 2181.19  5017.2 2181.60  5022.7 2185.75  5120.3 2184.64  5220.3 2188.93
  5240.7 2192.53  5312.4 2217.05  5336.5 2221.86  5393.7 2231.63  5404.4 2231.25
#Mann=4,-1,0
  4457.3    0.16       0  4961.0    0.07       0  4965.0    0.16       0
  5336.5    0.07       0
Bank Sta=4961,4965
Exp/Cntr=0.3,0.1

Chan Stop Cuts=-1