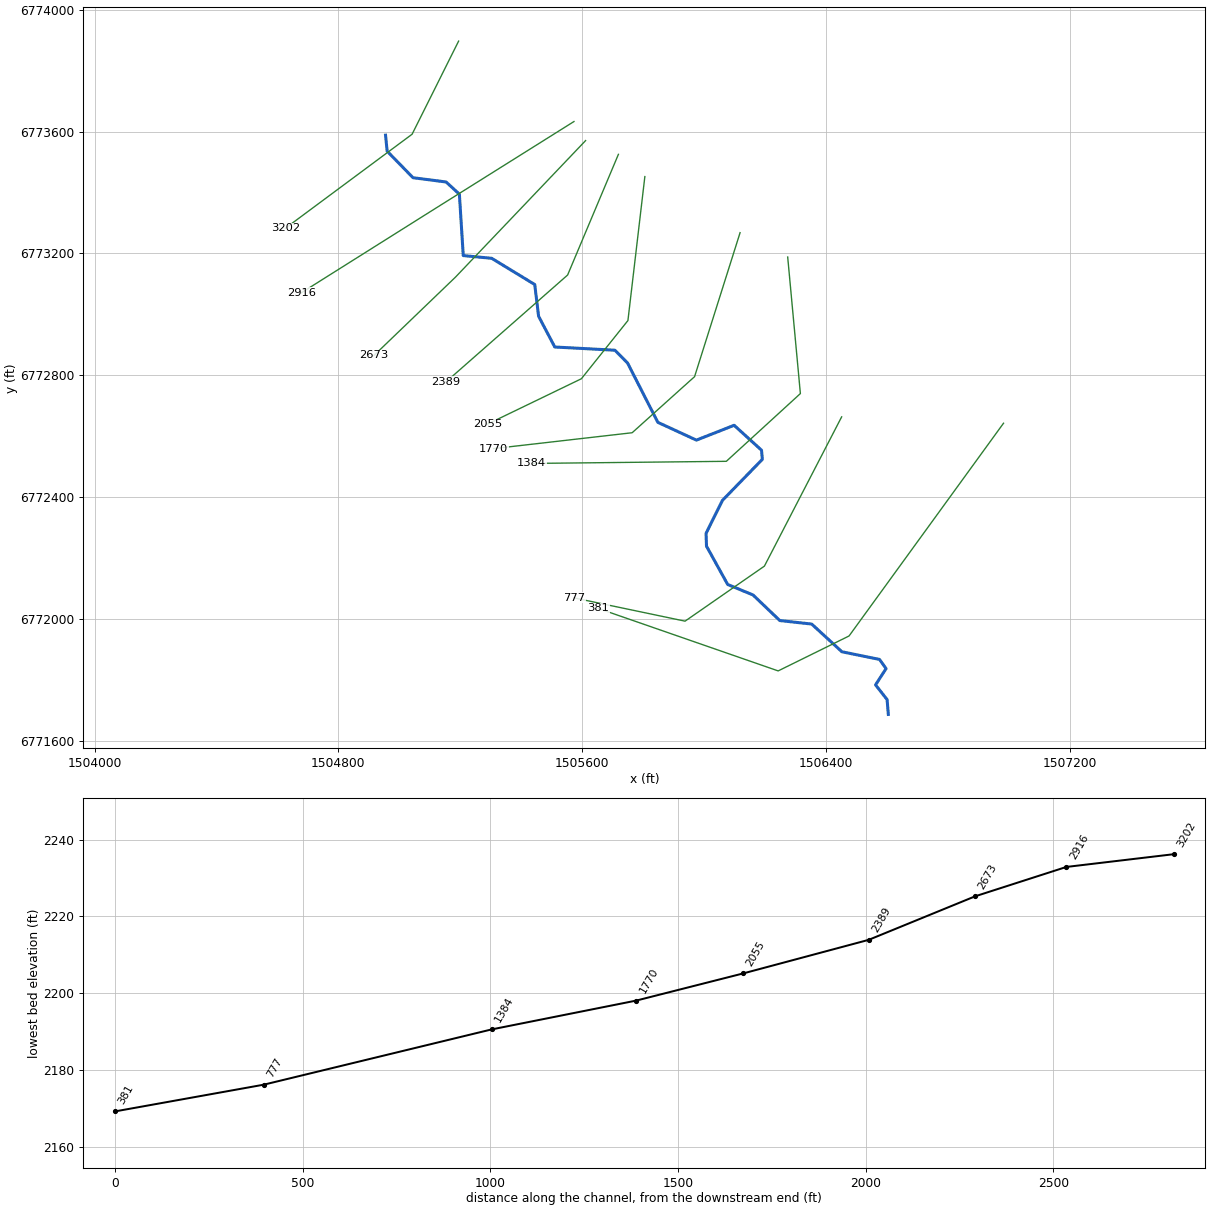
--- Elm 43.prj (project) ---

Proj Title=Elm 43 Base Level Engineering
Current Plan=p01
Default Exp/Contr=0.3,0.1
English Units
Geom File=g01
Flow File=f01
Plan File=p01
BEGIN DESCRIPTION:
Elm 43
END DESCRIPTION:

--- Elm 43.p01 (plan) ---

Plan Title=Multiple Run
Short Identifier=Multiple
Geom File=g01
Flow File=f01
Subcritical Flow
K Sum by GR= 0
Std Step Tol= 0.01
Critical Tol= 0.01
Num of Std Step Trials= 20
Max Error Tol= 0.3
Flow Tol Ratio= 0.001
Split Flow NTrial= 30
Split Flow Tol= 0.02
Split Flow Ratio= 0.02
Log Output Level= 0
Friction Slope Method= 1
Unsteady Friction Slope Method= 2
Unsteady Bridges Friction Slope Method= 1
Parabolic Critical Depth
Global Vel Dist=  1 , 1 , 1
Global Log Level= 0
CheckData=True
Encroach Param= -1, 0, 0, 0
BEGIN DESCRIPTION:
Multiple Run
END DESCRIPTION:

--- Elm 43.f01 (steady flow) ---

Flow Title=Multiple
Number of Profiles=7
Profile Names=10-year,25-year,50-year,1pct_min,100-year,1pct_plu,500-year
River Rch & RM= Elm 43,Reach-1,3202
     129     174     210     158     254     349     373
Boundary for River Rch & Prof#=Elm 43,Reach-1,1
Up Type=0
Dn Type=3
Dn Slope=0.005
Boundary for River Rch & Prof#=Elm 43,Reach-1,2
Up Type=0
Dn Type=3
Dn Slope=0.005
Boundary for River Rch & Prof#=Elm 43,Reach-1,3
Up Type=0
Dn Type=3
Dn Slope=0.005
Boundary for River Rch & Prof#=Elm 43,Reach-1,4
Up Type=0
Dn Type=3
Dn Slope=0.005
Boundary for River Rch & Prof#=Elm 43,Reach-1,5
Up Type=0
Dn Type=3
Dn Slope=0.005
Boundary for River Rch & Prof#=Elm 43,Reach-1,6
Up Type=0
Dn Type=3
Dn Slope=0.005
Boundary for River Rch & Prof#=Elm 43,Reach-1,7
Up Type=0
Dn Type=3
Dn Slope=0.005

--- Elm 43.g01 (geometry) ---

Geom Title=Existing Conditions

River Reach=Elm 43,Reach-1
Reach XY= 30
      1504955.00      6773588.00      1504960.30      6773535.46
      1505045.19      6773448.50      1505153.75      6773434.49
      1505197.32      6773394.52      1505210.03      6773193.08
      1505303.34      6773184.14      1505444.62      6773098.11
      1505457.32      6772993.94      1505510.41      6772893.17
      1505707.70      6772882.64      1505749.29      6772840.58
      1505848.66      6772646.02      1505975.18      6772587.71
      1506098.98      6772636.38      1506188.82      6772554.71
      1506191.59      6772524.67      1506060.83      6772390.30
      1506006.79      6772281.89      1506008.34      6772239.72
      1506077.85      6772114.16      1506161.02      6772079.81
      1506248.84      6771995.88      1506353.50      6771984.37
      1506452.59      6771893.54      1506576.05      6771868.38
      1506597.58      6771838.25      1506563.01      6771784.76
      1506601.02      6771736.65      1506605.00      6771688.00

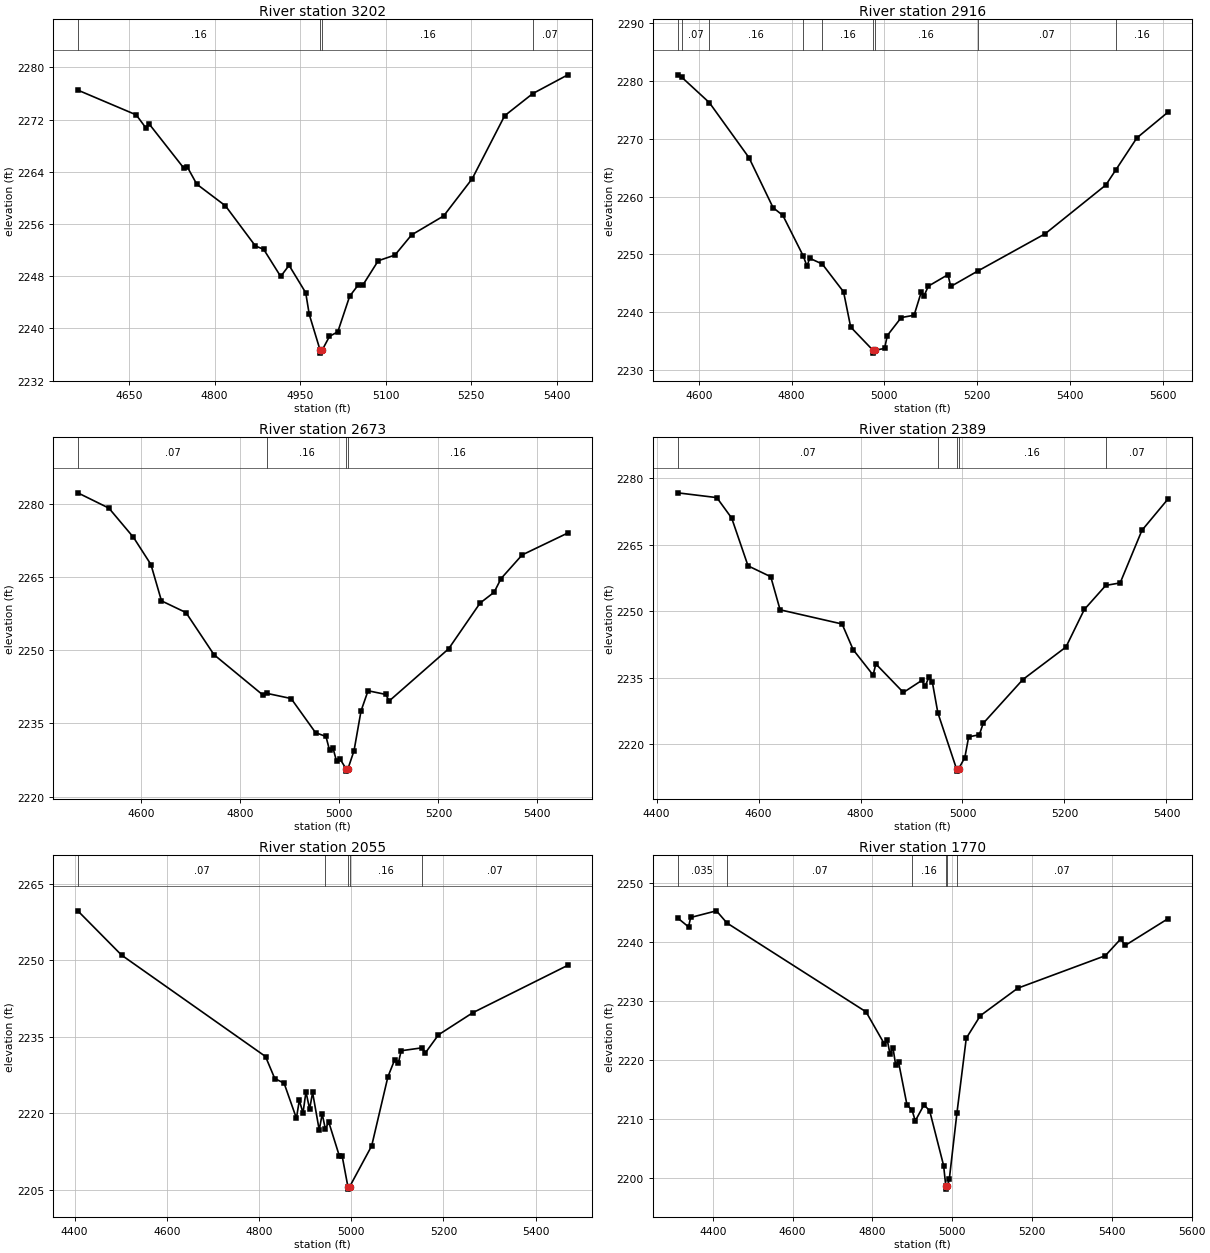
Type RM Length L Ch R = 1,3202,286,286,286
BEGIN DESCRIPTION:
elmc349
END DESCRIPTION:
XS GIS Cut Line= 3
      1505194.87      6773896.64      1505042.11      6773591.13
      1504626.04      6773282.53
#Sta/Elev= 30
  4560.1 2276.52  4662.6 2272.72  4679.4 2270.74  4685.0 2271.36  4746.5 2264.51
  4752.1 2264.75  4768.8 2262.10  4819.1 2258.78  4871.6 2252.63  4886.2 2252.11
  4916.0 2247.95  4930.7 2249.66  4959.9 2245.46  4966.1 2242.14  4985.0 2236.70
  4985.2 2236.20  4989.0 2236.70  5001.6 2238.77  5016.2 2239.47  5037.0 2244.92
  5051.7 2246.61  5059.9 2246.60  5087.1 2250.36  5116.4 2251.23  5145.6 2254.32
  5201.9 2257.23  5252.0 2262.94  5308.9 2272.59  5358.1 2275.98  5419.7 2278.86
#Mann=4,-1,0
  4560.1    0.16       0  4985.0    0.07       0  4989.0    0.16       0
  5358.1    0.07       0
Bank Sta=4985,4989
Exp/Cntr=0.3,0.1

Type RM Length L Ch R = 1,2916,243,243,243
BEGIN DESCRIPTION:
elmc348
END DESCRIPTION:
XS GIS Cut Line= 3
      1505573.39      6773632.81      1505108.09      6773341.13
      1504678.73      6773071.05
#Sta/Elev= 30
  4554.4 2281.08  4563.3 2280.66  4622.8 2276.26  4708.2 2266.73  4760.1 2258.08
  4781.3 2256.72  4825.2 2249.70  4833.2 2247.95  4839.1 2249.31  4866.2 2248.31
  4912.1 2243.49  4927.4 2237.40  4975.4 2233.38  4975.6 2232.88  4979.4 2233.38
  5000.5 2233.69  5006.4 2235.93  5036.4 2239.04  5064.1 2239.44  5079.5 2243.44
  5085.4 2242.77  5094.8 2244.48  5137.2 2246.47  5143.1 2244.42  5201.0 2247.08
  5346.8 2253.56  5477.5 2262.00  5498.7 2264.58  5544.3 2270.15  5610.8 2274.57
#Mann=9,-1,0
  4554.4    0.16       0  4563.3    0.07       0  4622.8    0.16       0
  4825.2    0.07       0  4866.2    0.16       0  4975.4    0.07       0
  4979.4    0.16       0  5201.0    0.07       0  5498.7    0.16       0
Bank Sta=4975.4,4979.4
Exp/Cntr=0.3,0.1

Type RM Length L Ch R = 1,2673,284,284,284
BEGIN DESCRIPTION:
elmc347
END DESCRIPTION:
XS GIS Cut Line= 3
      1505611.57      6773570.31      1505184.47      6773122.38
      1504917.13      6772865.45
#Sta/Elev= 30
  4471.7 2282.19  4534.5 2279.06  4584.2 2273.07  4619.4 2267.52  4640.7 2260.08
  4690.2 2257.68  4746.8 2249.06  4845.9 2240.78  4854.3 2241.13  4902.5 2240.09
  4951.9 2233.10  4972.9 2232.32  4980.2 2229.49  4987.1 2229.97  4994.3 2227.25
  5001.3 2227.71  5013.4 2225.73  5013.7 2225.23  5017.4 2225.73  5029.6 2229.41
  5043.7 2237.53  5057.9 2241.68  5093.7 2240.93  5100.5 2239.58  5220.6 2250.26
  5284.2 2259.63  5312.5 2261.84  5326.6 2264.65  5369.1 2269.48  5461.4 2273.97
#Mann=4,-1,0
  4471.7    0.07       0  4854.3    0.16       0  5013.4    0.07       0
  5017.4    0.16       0
Bank Sta=5013.4,5017.4
Exp/Cntr=0.3,0.1

Type RM Length L Ch R = 1,2389,334,334,334
BEGIN DESCRIPTION:
elmc346
END DESCRIPTION:
XS GIS Cut Line= 3
      1505719.21      6773525.19      1505552.53      6773129.32
      1505153.20      6772778.60
#Sta/Elev= 30
  4441.4 2276.73  4518.2 2275.65  4547.4 2271.02  4579.4 2260.24  4624.0 2257.78
  4642.3 2250.31  4763.9 2247.10  4785.6 2241.30  4824.7 2235.57  4830.1 2238.08
  4884.1 2231.64  4920.1 2234.35  4926.7 2233.04  4934.2 2235.10  4941.0 2233.90
  4951.7 2227.04  4988.3 2214.37  4988.6 2213.87  4992.3 2214.37  5004.6 2216.94
  5012.1 2221.61  5033.0 2222.08  5040.6 2224.66  5118.4 2234.56  5202.9 2241.90
  5238.9 2250.38  5281.0 2255.82  5309.2 2256.38  5351.9 2268.26  5402.4 2275.25
#Mann=5,-1,0
  4441.4    0.07       0  4951.7    0.16       0  4988.3    0.07       0
  4992.3    0.16       0  5281.0    0.07       0
Bank Sta=4988.3,4992.3
Exp/Cntr=0.3,0.1

Type RM Length L Ch R = 1,2055,285,285,285
BEGIN DESCRIPTION:
elmc345
END DESCRIPTION:
XS GIS Cut Line= 4
      1505806.00      6773452.22      1505750.45      6772980.01
      1505597.67      6772789.04      1505289.30      6772640.06
#Sta/Elev= 30
  4407.1 2259.69  4502.0 2251.01  4814.1 2231.13  4834.2 2226.80  4854.4 2225.90
  4881.1 2219.03  4887.4 2222.54  4895.4 2220.06  4901.8 2224.21  4909.8 2220.82
  4916.2 2224.08  4930.6 2216.70  4937.0 2219.88  4943.7 2216.98  4951.4 2218.22
  4973.9 2211.72  4980.3 2211.62  4992.7 2205.63  4992.9 2205.13  4996.7 2205.63
  5044.3 2213.61  5079.5 2227.16  5093.9 2230.42  5101.9 2229.79  5108.3 2232.26
  5153.3 2232.83  5160.9 2231.86  5189.1 2235.38  5263.4 2239.71  5469.6 2249.01
#Mann=5,-1,0
  4407.1    0.07       0  4943.7    0.16       0  4992.7    0.07       0
  4996.7    0.16       0  5153.3    0.07       0
Bank Sta=4992.7,4996.7
Exp/Cntr=0.3,0.1

Type RM Length L Ch R = 1,1770,386,386,386
BEGIN DESCRIPTION:
elmc344
END DESCRIPTION:
XS GIS Cut Line= 4
      1506118.50      6773268.20      1505969.20      6772795.99
      1505764.34      6772611.96      1505309.74      6772559.91
#Sta/Elev= 30
  4311.7 2244.11  4339.0 2242.59  4344.3 2244.19  4408.9 2245.32  4435.3 2243.25
  4783.9 2228.16  4829.6 2222.73  4837.1 2223.37  4843.8 2221.05  4851.3 2222.09
  4858.0 2219.19  4865.5 2219.58  4886.4 2212.39  4899.4 2211.42  4907.3 2209.65
  4929.0 2212.35  4943.2 2211.39  4978.3 2202.05  4983.8 2198.55  4984.1 2198.05
  4987.8 2198.55  4992.5 2199.70  5011.6 2210.93  5035.1 2223.68  5070.3 2227.51
  5164.1 2232.18  5383.6 2237.70  5421.8 2240.51  5434.0 2239.47  5539.9 2243.95
#Mann=6,-1,0
  4311.7   0.035       0  4435.3    0.07       0  4899.4    0.16       0
  4983.8    0.07       0  4987.8    0.16       0  5011.6    0.07       0
Bank Sta=4983.8,4987.8
Exp/Cntr=0.3,0.1

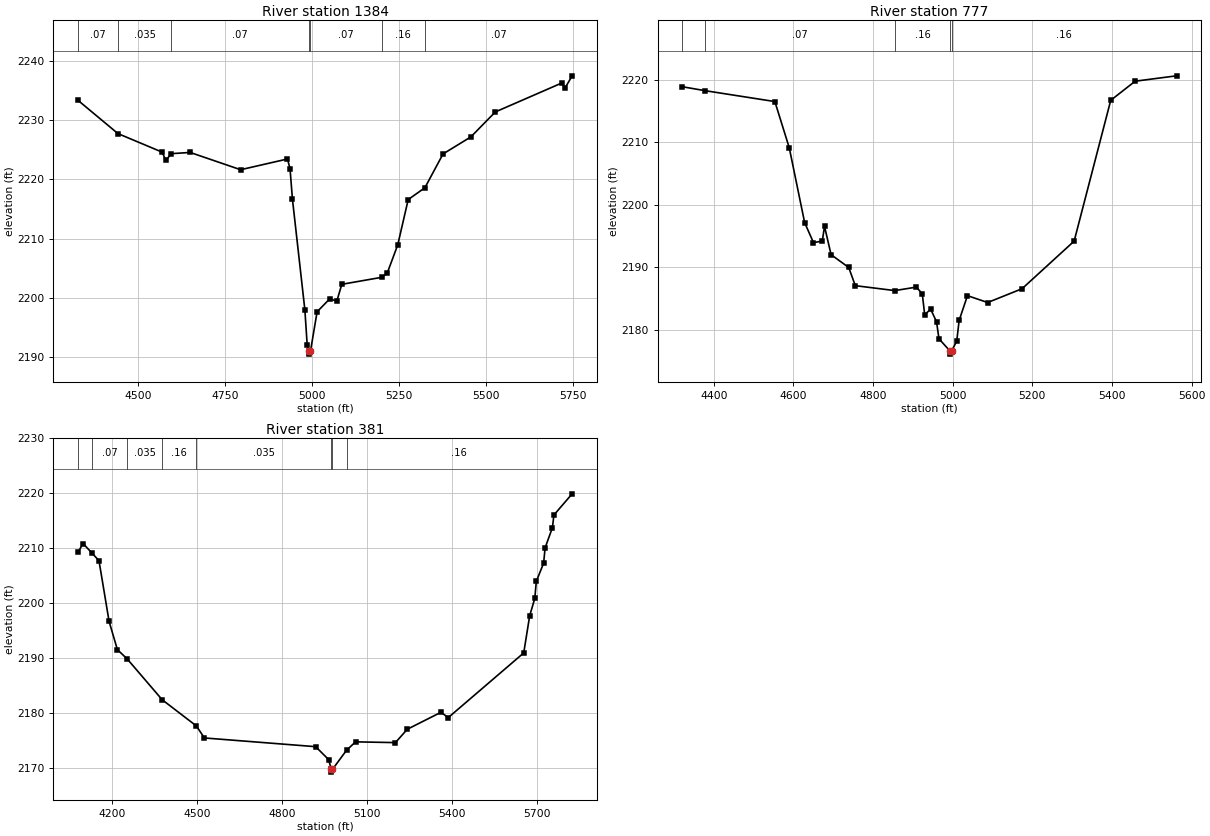
Type RM Length L Ch R = 1,1384,607,607,607
BEGIN DESCRIPTION:
elmc343
END DESCRIPTION:
XS GIS Cut Line= 4
      1506274.75      6773188.32      1506316.42      6772740.43
      1506073.36      6772518.21      1505434.46      6772511.26
#Sta/Elev= 30
  4328.4 2233.29  4442.8 2227.70  4569.8 2224.57  4579.8 2223.18  4596.4 2224.32
  4650.1 2224.52  4794.9 2221.61  4929.3 2223.42  4936.7 2221.79  4943.5 2216.70
  4979.3 2197.97  4986.0 2192.01  4991.4 2191.02  4991.7 2190.52  4995.4 2191.02
  5014.4 2197.66  5050.2 2199.81  5071.1 2199.48  5085.3 2202.29  5199.8 2203.47
  5215.9 2204.21  5245.9 2208.95  5275.9 2216.58  5323.8 2218.57  5375.9 2224.27
  5455.9 2227.15  5525.9 2231.35  5716.0 2236.21  5726.0 2235.38  5746.5 2237.44
#Mann=7,-1,0
  4328.4    0.07       0  4442.8   0.035       0  4596.4    0.07       0
  4991.4    0.07       0  4995.4    0.07       0  5199.8    0.16       0
  5323.8    0.07       0
Bank Sta=4991.4,4995.4
Exp/Cntr=0.3,0.1

Type RM Length L Ch R = 1,777,396,396,396
BEGIN DESCRIPTION:
elmc342
END DESCRIPTION:
XS GIS Cut Line= 4
      1506451.82      6772664.01      1506198.36      6772174.46
      1505937.95      6771993.90      1505573.32      6772070.30
#Sta/Elev= 30
  4321.3 2218.92  4377.4 2218.30  4553.3 2216.55  4589.5 2209.14  4628.1 2197.17
  4650.3 2193.97  4672.4 2194.22  4678.0 2196.57  4694.5 2192.04  4738.8 2189.99
  4755.3 2187.08  4854.6 2186.29  4908.7 2186.85  4923.5 2185.77  4929.6 2182.42
  4944.5 2183.32  4959.3 2181.31  4965.4 2178.58  4993.1 2176.62  4993.4 2176.12
  4997.1 2176.62  5010.0 2178.19  5016.1 2181.52  5037.0 2185.48  5087.7 2184.38
  5174.1 2186.59  5304.9 2194.21  5396.8 2216.75  5458.1 2219.81  5562.0 2220.67
#Mann=5,-1,0
  4321.3    0.16       0  4377.4    0.07       0  4854.6    0.16       0
  4993.1    0.07       0  4997.1    0.16       0
Bank Sta=4993.1,4997.1
Exp/Cntr=0.3,0.1

Type RM Length L Ch R = 1,381,0,0,0
BEGIN DESCRIPTION:
elmc341
END DESCRIPTION:
XS GIS Cut Line= 4
      1506983.07      6772643.18      1506476.14      6771945.29
      1506243.50      6771830.71      1505653.24      6772035.56
#Sta/Elev= 30
  4078.6 2209.27  4096.0 2210.83  4128.6 2209.04  4152.4 2207.70  4188.0 2196.66
  4217.4 2191.49  4252.2 2189.79  4375.7 2182.36  4496.7 2177.58  4525.0 2175.39
  4918.4 2173.80  4964.1 2171.46  4973.9 2169.66  4974.1 2169.16  4977.9 2169.66
  5027.5 2173.14  5059.5 2174.68  5200.5 2174.54  5242.3 2176.97  5361.5 2180.07
  5387.3 2179.10  5654.1 2190.89  5675.2 2197.68  5693.3 2200.83  5698.6 2203.94
  5724.4 2207.24  5729.7 2210.05  5755.6 2213.73  5760.8 2216.03  5825.3 2219.89
#Mann=8,-1,0
  4078.6    0.16       0  4128.6    0.07       0  4252.2   0.035       0
  4375.7    0.16       0  4496.7   0.035       0  4973.9   0.035       0
  4977.9   0.035       0  5027.5    0.16       0
Bank Sta=4973.9,4977.9
Exp/Cntr=0.3,0.1

Chan Stop Cuts=-1