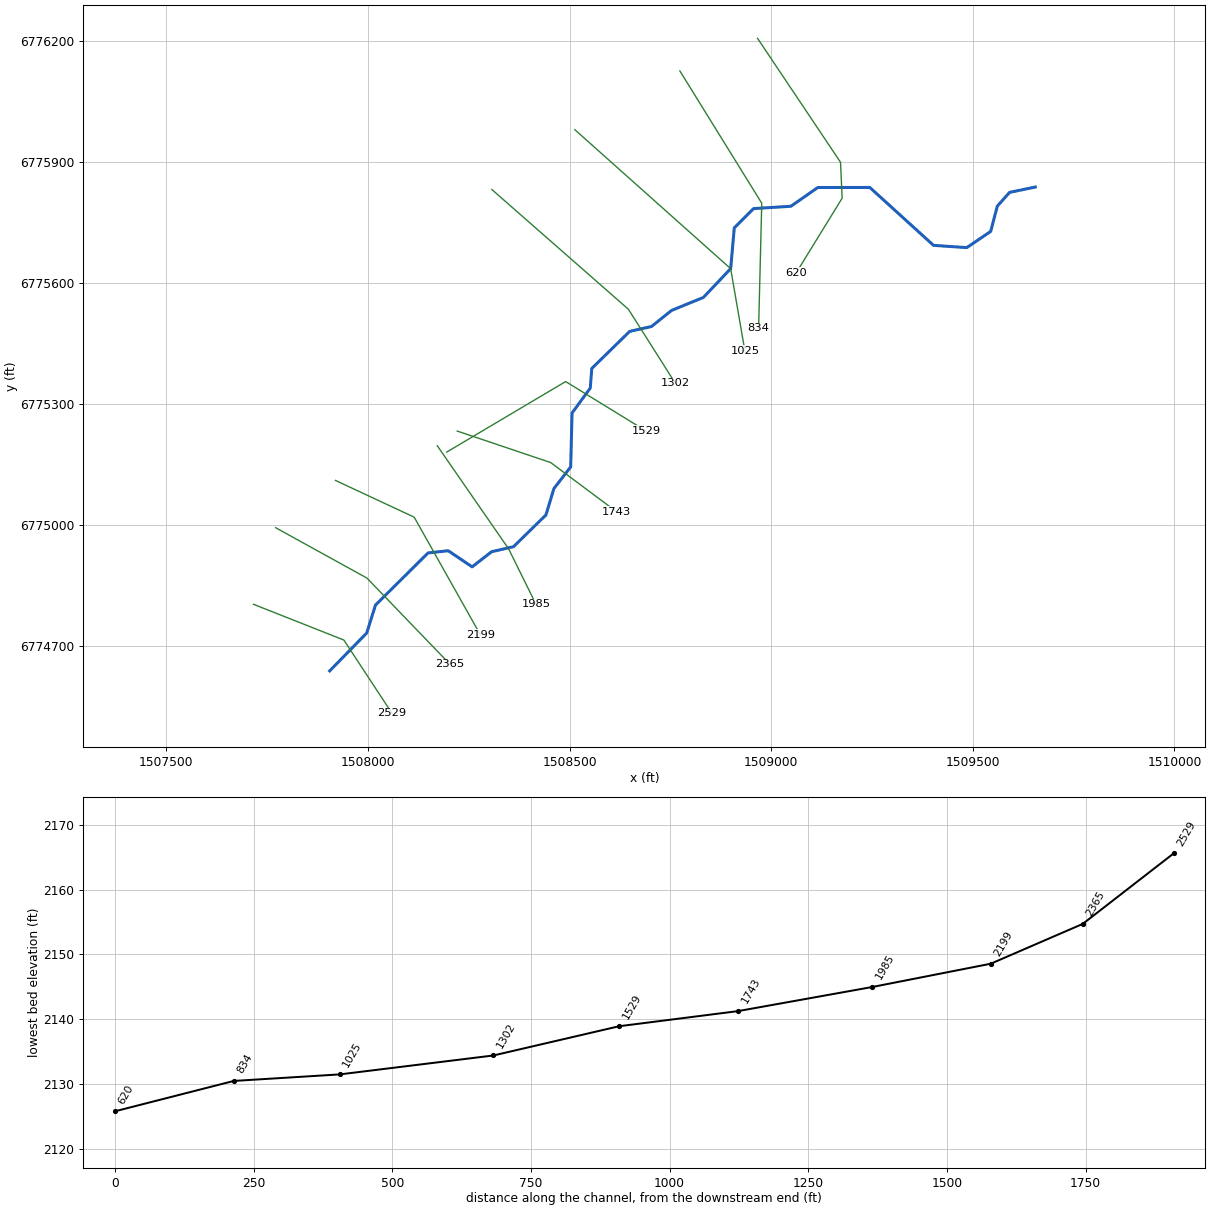
--- Elm 44.prj (project) ---

Proj Title=Elm 44 Base Level Engineering
Current Plan=p01
Default Exp/Contr=0.3,0.1
English Units
Geom File=g01
Flow File=f01
Plan File=p01
BEGIN DESCRIPTION:
Elm 44
END DESCRIPTION:

--- Elm 44.p01 (plan) ---

Plan Title=Multiple Run
Short Identifier=Multiple
Geom File=g01
Flow File=f01
Subcritical Flow
K Sum by GR= 0
Std Step Tol= 0.01
Critical Tol= 0.01
Num of Std Step Trials= 20
Max Error Tol= 0.3
Flow Tol Ratio= 0.001
Split Flow NTrial= 30
Split Flow Tol= 0.02
Split Flow Ratio= 0.02
Log Output Level= 0
Friction Slope Method= 1
Unsteady Friction Slope Method= 2
Unsteady Bridges Friction Slope Method= 1
Parabolic Critical Depth
Global Vel Dist=  1 , 1 , 1
Global Log Level= 0
CheckData=True
Encroach Param= -1, 0, 0, 0
BEGIN DESCRIPTION:
Multiple Run
END DESCRIPTION:

--- Elm 44.f01 (steady flow) ---

Flow Title=Multiple
Number of Profiles=7
Profile Names=10-year,25-year,50-year,1pct_min,100-year,1pct_plu,500-year
River Rch & RM= Elm 44,Reach-1,2529
      99     132     158     118     190     261     275
River Rch & RM= Elm 44,Reach-1,1302
     139     188     228     173     277     381     411
Boundary for River Rch & Prof#=Elm 44,Reach-1,1
Up Type=0
Dn Type=3
Dn Slope=0.005
Boundary for River Rch & Prof#=Elm 44,Reach-1,2
Up Type=0
Dn Type=3
Dn Slope=0.005
Boundary for River Rch & Prof#=Elm 44,Reach-1,3
Up Type=0
Dn Type=3
Dn Slope=0.005
Boundary for River Rch & Prof#=Elm 44,Reach-1,4
Up Type=0
Dn Type=3
Dn Slope=0.005
Boundary for River Rch & Prof#=Elm 44,Reach-1,5
Up Type=0
Dn Type=3
Dn Slope=0.005
Boundary for River Rch & Prof#=Elm 44,Reach-1,6
Up Type=0
Dn Type=3
Dn Slope=0.005
Boundary for River Rch & Prof#=Elm 44,Reach-1,7
Up Type=0
Dn Type=3
Dn Slope=0.005

--- Elm 44.g01 (geometry) ---

Geom Title=Existing Conditions

River Reach=Elm 44,Reach-1
Reach XY= 30
      1507905.00      6774638.00      1507996.89      6774731.93
      1508018.63      6774801.21      1508148.95      6774930.50
      1508198.95      6774936.02      1508258.31      6774896.07
      1508306.65      6774933.55      1508361.07      6774946.11
      1508441.39      6775024.76      1508461.14      6775090.17
      1508502.75      6775143.93      1508506.13      6775277.53
      1508551.35      6775339.51      1508555.00      6775388.00
      1508648.92      6775479.91      1508703.27      6775492.18
      1508752.81      6775531.90      1508831.89      6775564.26
      1508899.48      6775635.56      1508908.51      6775736.75
      1508956.25      6775784.49      1509049.02      6775790.36
      1509115.51      6775836.80      1509244.56      6775836.96
      1509402.58      6775693.39      1509485.05      6775687.74
      1509544.38      6775727.94      1509560.72      6775790.48
      1509591.22      6775824.73      1509655.00      6775838.00

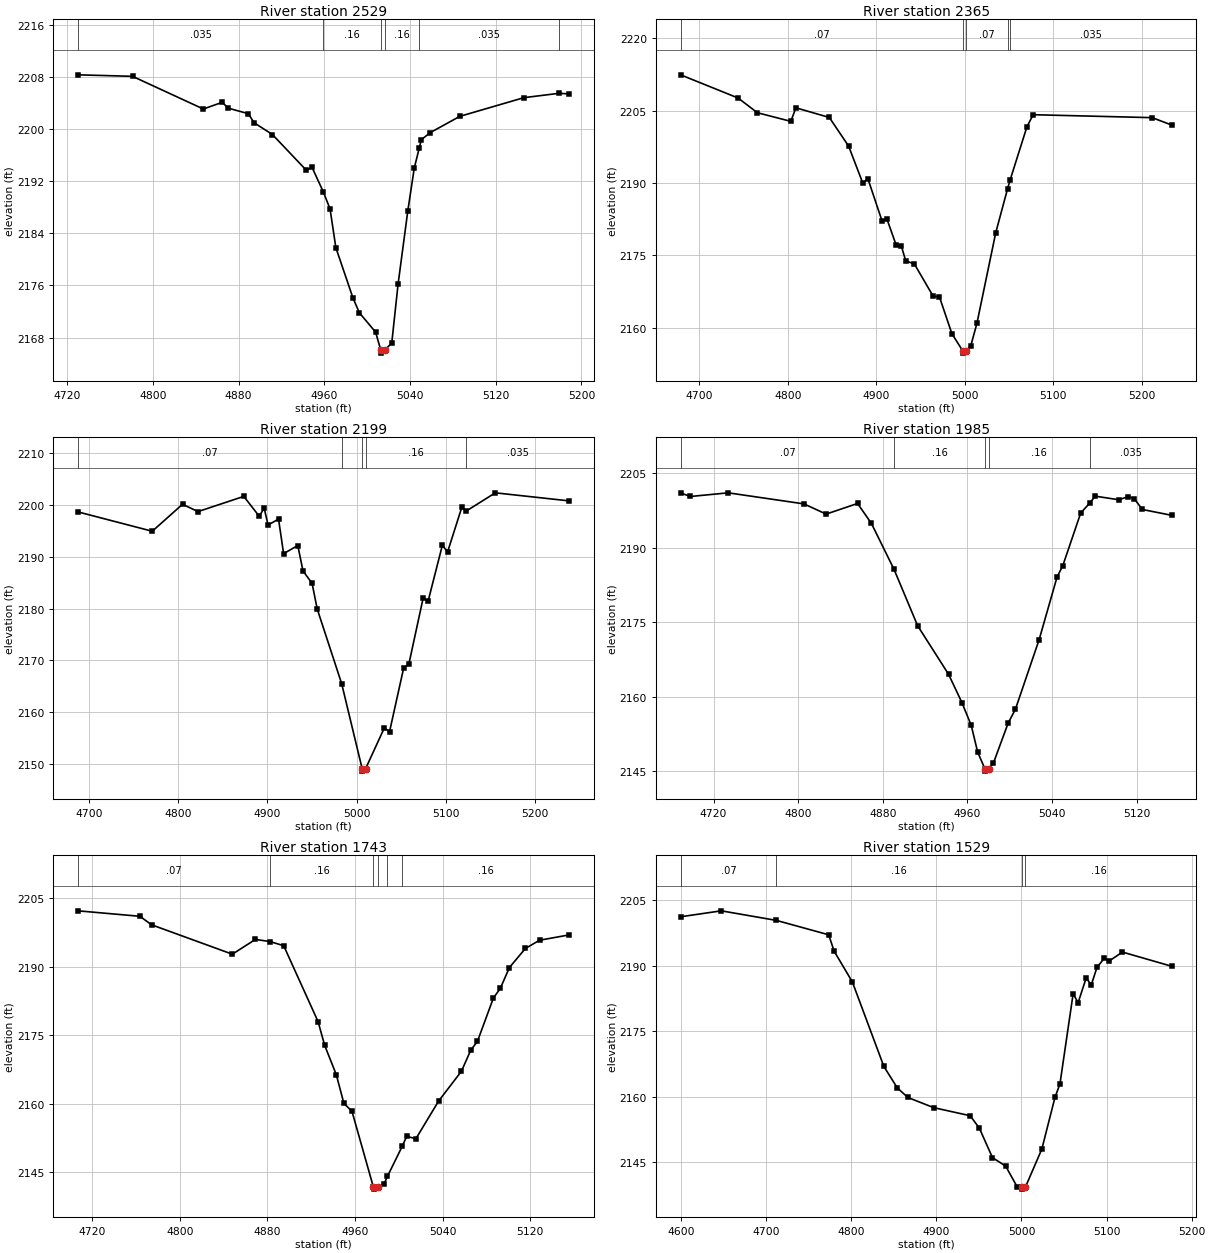
Type RM Length L Ch R = 1,2529,164,164,164
BEGIN DESCRIPTION:
elmc215
END DESCRIPTION:
XS GIS Cut Line= 3
      1507716.20      6774803.10      1507940.16      6774714.56
      1508059.70      6774532.65
#Sta/Elev= 30
  4730.1 2208.35  4781.0 2208.12  4847.1 2203.10  4864.8 2204.13  4870.2 2203.24
  4889.1 2202.38  4894.5 2200.99  4911.6 2199.18  4943.2 2193.70  4948.6 2194.13
  4959.0 2190.41  4965.4 2187.75  4970.8 2181.81  4986.8 2174.07  4992.8 2171.79
  5007.9 2168.83  5012.7 2166.10  5012.9 2165.60  5016.7 2166.10  5023.0 2167.16
  5028.9 2176.21  5038.0 2187.48  5044.0 2194.01  5048.7 2197.13  5050.6 2198.39
  5059.1 2199.49  5086.5 2201.97  5146.3 2204.84  5179.1 2205.51  5188.6 2205.42
#Mann=6,-1,0
  4730.1   0.035       0  4959.0    0.16       0  5012.7    0.07       0
  5016.7    0.16       0  5048.7   0.035       0  5179.1    0.07       0
Bank Sta=5012.7,5016.7
Exp/Cntr=0.3,0.1

Type RM Length L Ch R = 1,2365,166,166,166
BEGIN DESCRIPTION:
elmc352
END DESCRIPTION:
XS GIS Cut Line= 3
      1507770.92      6774993.19      1507997.45      6774868.21
      1508203.15      6774654.69
#Sta/Elev= 30
  4678.8 2212.42  4743.8 2207.61  4765.6 2204.56  4803.4 2202.77  4809.1 2205.58
  4846.9 2203.58  4868.7 2197.64  4884.8 2189.93  4890.5 2190.88  4906.5 2182.11
  4912.2 2182.42  4922.6 2177.03  4928.3 2176.91  4933.3 2173.83  4943.0 2173.21
  4964.3 2166.50  4971.3 2166.41  4985.4 2158.76  4997.6 2155.21  4997.8 2154.71
  5001.6 2155.21  5006.8 2156.23  5013.7 2160.86  5035.0 2179.68  5048.4 2188.82
  5051.1 2190.52  5070.3 2201.67  5077.3 2204.15  5211.8 2203.54  5234.0 2202.00
#Mann=5,-1,0
  4678.8    0.07       0  4997.6    0.07       0  5001.6    0.07       0
  5048.4    0.16       0  5051.1   0.035       0
Bank Sta=4997.6,5001.6
Exp/Cntr=0.3,0.1

Type RM Length L Ch R = 1,2199,214,214,214
BEGIN DESCRIPTION:
elmc351
END DESCRIPTION:
XS GIS Cut Line= 3
      1507919.35      6775110.38      1508114.64      6775019.25
      1508278.67      6774727.63
#Sta/Elev= 30
  4687.9 2198.69  4771.1 2194.95  4805.0 2200.17  4822.3 2198.75  4873.6 2201.69
  4890.9 2197.85  4896.4 2199.43  4900.8 2196.15  4912.5 2197.31  4918.2 2190.62
  4934.1 2192.19  4939.9 2187.28  4950.1 2184.87  4955.8 2179.93  4983.2 2165.48
  5006.1 2149.06  5006.4 2148.56  5010.1 2149.06  5031.0 2156.92  5036.8 2156.16
  5052.7 2168.55  5058.4 2169.21  5074.4 2181.97  5080.1 2181.48  5096.0 2192.25
  5101.8 2190.93  5117.7 2199.55  5122.4 2198.82  5155.3 2202.38  5238.0 2200.82
#Mann=5,-1,0
  4687.9    0.07       0  4983.2    0.16       0  5006.1    0.07       0
  5010.1    0.16       0  5122.4   0.035       0
Bank Sta=5006.1,5010.1
Exp/Cntr=0.3,0.1

Type RM Length L Ch R = 1,1985,242,242,242
BEGIN DESCRIPTION:
elmc214
END DESCRIPTION:
XS GIS Cut Line= 3
      1508171.90      6775196.37      1508348.96      6774940.45
      1508416.74      6774803.06
#Sta/Elev= 30
  4688.8 2201.06  4698.0 2200.34  4733.8 2201.08  4805.4 2198.85  4826.4 2196.79
  4856.1 2198.93  4869.2 2194.91  4890.6 2185.64  4912.9 2174.28  4942.2 2164.47
  4954.8 2158.77  4963.6 2154.17  4969.6 2148.84  4976.4 2145.46  4976.7 2144.96
  4980.4 2145.46  4984.5 2146.55  4998.5 2154.66  5005.3 2157.41  5027.8 2171.49
  5044.7 2184.09  5050.2 2186.42  5067.1 2197.02  5075.5 2198.98  5080.8 2200.41
  5103.1 2199.68  5112.0 2200.32  5117.6 2199.92  5125.4 2197.72  5153.2 2196.54
#Mann=5,-1,0
  4688.8    0.07       0  4890.6    0.16       0  4976.4    0.07       0
  4980.4    0.16       0  5075.5   0.035       0
Bank Sta=4976.4,4980.4
Exp/Cntr=0.3,0.1

Type RM Length L Ch R = 1,1743,214,214,214
BEGIN DESCRIPTION:
elmc350
END DESCRIPTION:
XS GIS Cut Line= 3
      1508221.37      6775232.80      1508453.18      6775154.67
      1508616.75      6775032.63
#Sta/Elev= 30
  4707.0 2202.27  4763.6 2201.07  4774.2 2199.21  4848.0 2192.76  4869.1 2196.00
  4882.3 2195.53  4894.9 2194.63  4926.3 2177.99  4932.4 2172.74  4943.0 2166.32
  4949.9 2160.05  4957.3 2158.30  4976.8 2141.74  4977.1 2141.24  4980.8 2141.74
  4986.5 2142.31  4989.7 2144.04  5003.2 2150.64  5007.3 2152.81  5015.7 2152.30
  5036.5 2160.58  5057.3 2167.09  5065.7 2171.67  5071.9 2173.64  5086.5 2183.16
  5092.8 2185.26  5101.1 2189.83  5115.7 2194.01  5128.6 2195.82  5155.7 2196.99
#Mann=6,-1,0
  4707.0    0.07       0  4882.3    0.16       0  4976.8    0.07       0
  4980.8    0.16       0  4989.7    0.07       0  5003.2    0.16       0
Bank Sta=4976.8,4980.8
Exp/Cntr=0.3,0.1

Type RM Length L Ch R = 1,1529,227,227,227
BEGIN DESCRIPTION:
elmc213
END DESCRIPTION:
XS GIS Cut Line= 3
      1508195.37      6775180.71      1508490.30      6775355.58
      1508689.87      6775232.97
#Sta/Elev= 30
  4599.5 2201.17  4647.3 2202.53  4712.1 2200.34  4773.5 2197.05  4779.9 2193.30
  4801.3 2186.27  4838.3 2166.96  4854.0 2162.08  4866.5 2159.86  4896.8 2157.54
  4939.7 2155.69  4950.5 2152.85  4965.9 2146.11  4981.4 2144.17  4994.8 2139.48
  5000.7 2139.41  5000.9 2138.91  5004.7 2139.41  5023.9 2148.06  5039.4 2159.92
  5045.2 2162.96  5060.7 2183.60  5066.5 2181.52  5076.1 2187.24  5081.9 2185.54
  5088.7 2189.60  5097.4 2191.72  5103.2 2191.08  5118.6 2193.10  5176.6 2189.85
#Mann=4,-1,0
  4599.5    0.07       0  4712.1    0.16       0  5000.7    0.07       0
  5004.7    0.16       0
Bank Sta=5000.7,5004.7
Exp/Cntr=0.3,0.1

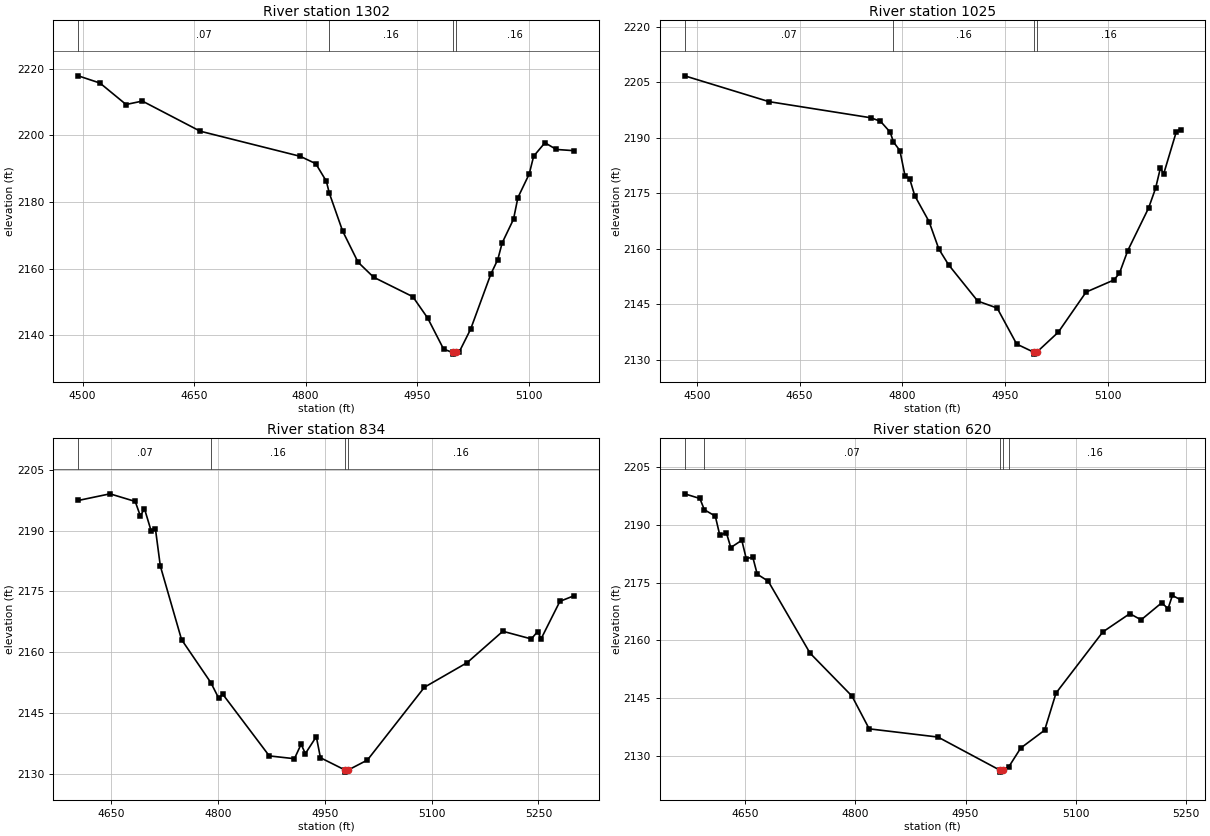
Type RM Length L Ch R = 1,1302,277,277,277
BEGIN DESCRIPTION:
elmc353
END DESCRIPTION:
XS GIS Cut Line= 3
      1508307.32      6775831.77      1508645.89      6775534.88
      1508762.11      6775351.51
#Sta/Elev= 30
  4494.0 2217.85  4523.3 2215.68  4558.4 2209.25  4580.3 2210.28  4658.1 2201.25
  4792.8 2193.71  4813.7 2191.50  4827.9 2186.25  4831.9 2182.68  4849.8 2171.32
  4870.6 2161.96  4891.5 2157.46  4944.3 2151.61  4964.3 2145.20  4985.7 2135.90
  4997.8 2134.89  4998.0 2134.39  5001.8 2134.89  5006.9 2135.12  5022.1 2141.88
  5049.2 2158.35  5058.6 2162.74  5064.5 2167.73  5079.8 2174.85  5085.7 2181.33
  5100.9 2188.40  5106.9 2193.75  5122.1 2197.78  5137.4 2195.77  5161.4 2195.40
#Mann=4,-1,0
  4494.0    0.07       0  4831.9    0.16       0  4997.8    0.07       0
  5001.8    0.16       0
Bank Sta=4997.8,5001.8
Exp/Cntr=0.3,0.1

Type RM Length L Ch R = 1,1025,191,191,191
BEGIN DESCRIPTION:
elmc212
END DESCRIPTION:
XS GIS Cut Line= 3
      1508513.04      6775980.21      1508899.48      6775635.56
      1508934.74      6775431.89
#Sta/Elev= 30
  4482.2 2206.68  4605.4 2199.70  4754.0 2195.35  4768.2 2194.40  4782.4 2191.46
  4787.2 2188.80  4796.6 2186.47  4804.1 2179.64  4810.8 2178.90  4818.3 2174.29
  4839.2 2167.29  4853.5 2159.87  4867.7 2155.62  4910.3 2145.81  4938.7 2143.92
  4967.2 2134.19  4992.4 2131.97  4992.7 2131.47  4996.4 2131.97  5028.0 2137.40
  5068.6 2148.24  5109.2 2151.50  5117.3 2153.31  5129.5 2159.45  5159.9 2170.95
  5170.1 2176.27  5177.0 2181.64  5182.1 2180.27  5200.5 2191.63  5206.7 2192.16
#Mann=4,-1,0
  4482.2    0.07       0  4787.2    0.16       0  4992.4    0.07       0
  4996.4    0.16       0
Bank Sta=4992.4,4996.4
Exp/Cntr=0.3,0.1

Type RM Length L Ch R = 1,834,214,214,214
BEGIN DESCRIPTION:
elmc354
END DESCRIPTION:
XS GIS Cut Line= 3
      1508773.51      6776125.99      1508976.61      6775797.90
      1508968.80      6775487.96
#Sta/Elev= 30
  4604.2 2197.44  4648.8 2199.08  4684.2 2197.20  4691.3 2193.65  4697.2 2195.38
  4706.7 2189.84  4712.5 2190.51  4719.4 2181.30  4749.2 2163.14  4790.3 2152.53
  4801.2 2148.74  4807.1 2149.65  4872.3 2134.46  4907.6 2133.77  4917.0 2137.35
  4922.9 2135.01  4938.3 2139.21  4944.1 2134.01  4978.8 2130.96  4979.0 2130.46
  4982.8 2130.96  5010.0 2133.44  5090.0 2151.39  5150.0 2157.46  5200.0 2165.19
  5240.0 2163.30  5248.8 2165.11  5253.8 2163.36  5280.1 2172.57  5300.1 2173.96
#Mann=4,-1,0
  4604.2    0.07       0  4790.3    0.16       0  4978.8    0.07       0
  4982.8    0.16       0
Bank Sta=4978.8,4982.8
Exp/Cntr=0.3,0.1

Type RM Length L Ch R = 1,620,0,0,0
BEGIN DESCRIPTION:
elmc211
END DESCRIPTION:
XS GIS Cut Line= 4
      1508966.17      6776206.79      1509171.93      6775899.46
      1509176.00      6775810.42      1509062.54      6775626.01
#Sta/Elev= 30
  4567.5 2198.06  4588.2 2196.85  4594.3 2193.92  4609.2 2192.27  4615.3 2187.34
  4624.3 2187.95  4630.3 2184.10  4645.3 2186.00  4651.3 2181.25  4660.3 2181.59
  4666.3 2177.19  4681.3 2175.37  4738.3 2156.67  4795.4 2145.52  4818.8 2137.02
  4912.5 2134.89  4996.9 2126.28  4997.1 2125.78  5000.9 2126.28  5008.9 2127.14
  5025.2 2132.03  5057.8 2136.67  5073.3 2146.32  5137.1 2162.20  5173.8 2166.94
  5189.2 2165.33  5217.2 2169.75  5225.9 2168.25  5231.8 2171.67  5243.0 2170.54
#Mann=5,-1,0
  4567.5    0.16       0  4594.3    0.07       0  4996.9    0.07       0
  5000.9    0.07       0  5008.9    0.16       0
Bank Sta=4996.9,5000.9
Exp/Cntr=0.3,0.1

Chan Stop Cuts=-1