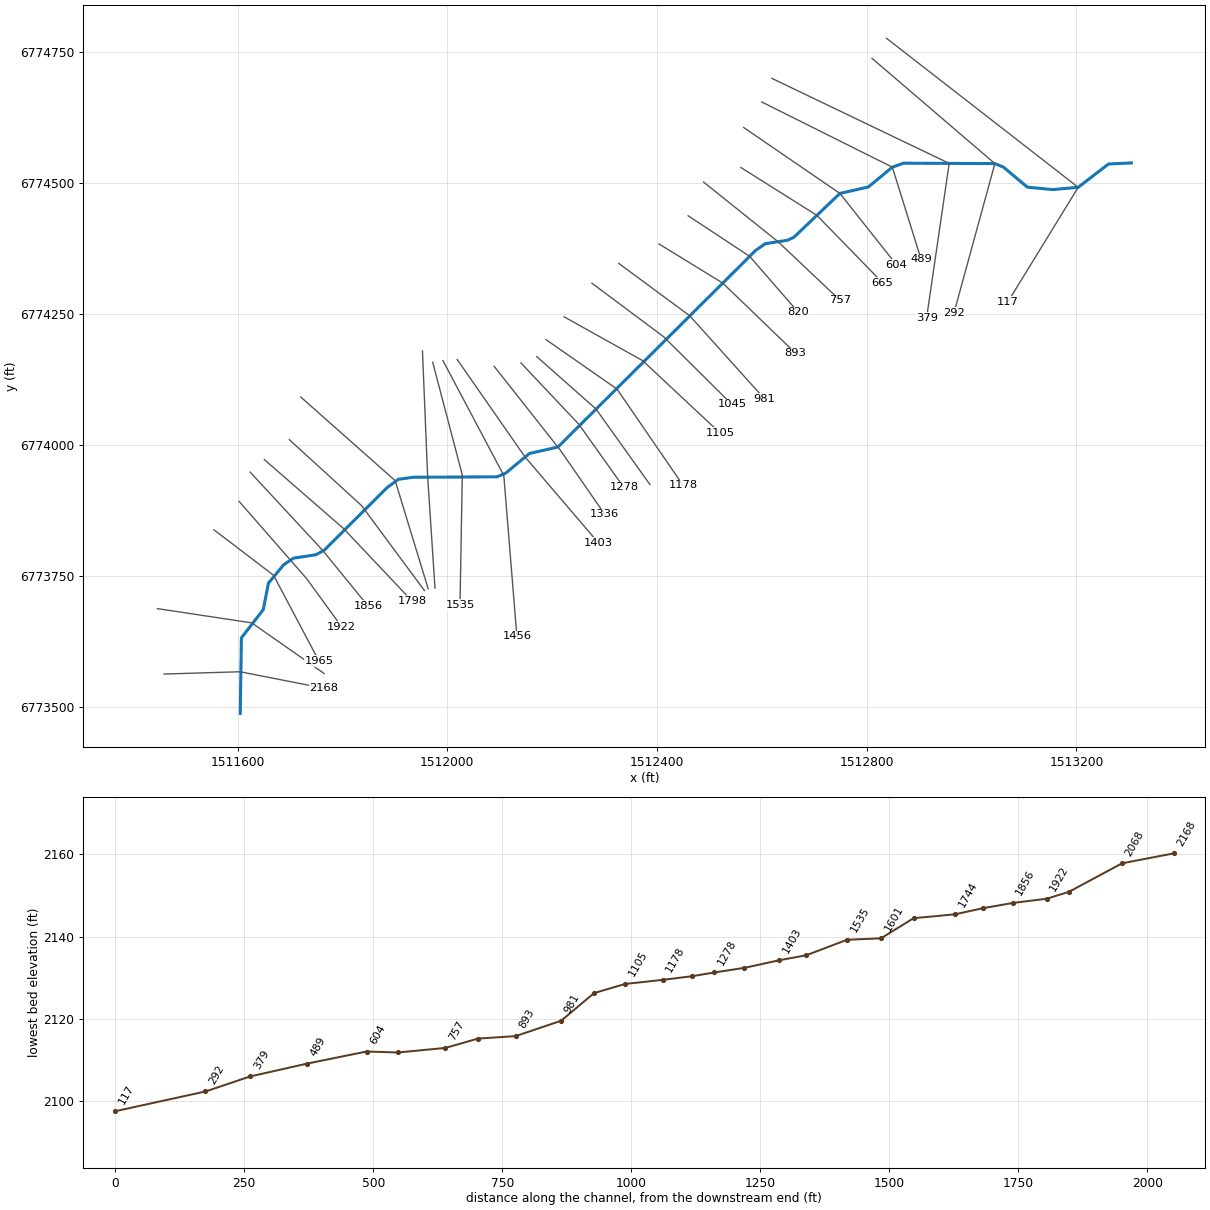
--- Elm 45.prj (project) ---

Proj Title=Elm 45 Base Level Engineering
Current Plan=p01
Default Exp/Contr=0.3,0.1
English Units
Geom File=g01
Flow File=f01
Plan File=p01
BEGIN DESCRIPTION:
Elm 45
END DESCRIPTION:

--- Elm 45.p01 (plan) ---

Plan Title=Multiple Run
Short Identifier=Multiple
Geom File=g01
Flow File=f01
Subcritical Flow
K Sum by GR= 0
Std Step Tol= 0.01
Critical Tol= 0.01
Num of Std Step Trials= 20
Max Error Tol= 0.3
Flow Tol Ratio= 0.001
Split Flow NTrial= 30
Split Flow Tol= 0.02
Split Flow Ratio= 0.02
Log Output Level= 0
Friction Slope Method= 1
Unsteady Friction Slope Method= 2
Unsteady Bridges Friction Slope Method= 1
Parabolic Critical Depth
Global Vel Dist=  1 , 1 , 1
Global Log Level= 0
CheckData=True
Encroach Param= -1, 0, 0, 0
BEGIN DESCRIPTION:
Multiple Run
END DESCRIPTION:

--- Elm 45.f01 (steady flow) ---

Flow Title=Multiple
Number of Profiles=7
Profile Names=10-year,25-year,50-year,1pct_min,100-year,1pct_plu,500-year
River Rch & RM= Elm 45,Reach-1,2168
     140     192     235     180     288     396     435
Boundary for River Rch & Prof#=Elm 45,Reach-1,1
Up Type=0
Dn Type=3
Dn Slope=0.005
Boundary for River Rch & Prof#=Elm 45,Reach-1,2
Up Type=0
Dn Type=3
Dn Slope=0.005
Boundary for River Rch & Prof#=Elm 45,Reach-1,3
Up Type=0
Dn Type=3
Dn Slope=0.005
Boundary for River Rch & Prof#=Elm 45,Reach-1,4
Up Type=0
Dn Type=3
Dn Slope=0.005
Boundary for River Rch & Prof#=Elm 45,Reach-1,5
Up Type=0
Dn Type=3
Dn Slope=0.005
Boundary for River Rch & Prof#=Elm 45,Reach-1,6
Up Type=0
Dn Type=3
Dn Slope=0.005
Boundary for River Rch & Prof#=Elm 45,Reach-1,7
Up Type=0
Dn Type=3
Dn Slope=0.005

--- Elm 45.g01 (geometry) ---

Geom Title=Existing Conditions

River Reach=Elm 45,Reach-1
Reach XY= 30
      1511605.00      6773488.00      1511607.19      6773632.09
      1511648.85      6773685.85      1511658.86      6773736.58
      1511687.95      6773771.51      1511706.43      6773784.11
      1511748.91      6773790.55      1511764.66      6773798.79
      1511884.84      6773918.39      1511906.46      6773934.46
      1511934.82      6773938.43      1512094.50      6773939.20
      1512111.08      6773946.09      1512156.75      6773983.78
      1512211.06      6773996.14      1512588.33      6774371.35
      1512606.65      6774384.03      1512648.95      6774390.54
      1512661.04      6774396.18      1512748.95      6774479.84
      1512803.25      6774492.22      1512848.92      6774529.91
      1512870.21      6774537.50      1513044.50      6774536.78
      1513061.06      6774529.85      1513106.60      6774491.70
      1513155.00      6774487.17      1513203.47      6774491.52
      1513261.27      6774536.01      1513305.00      6774538.00

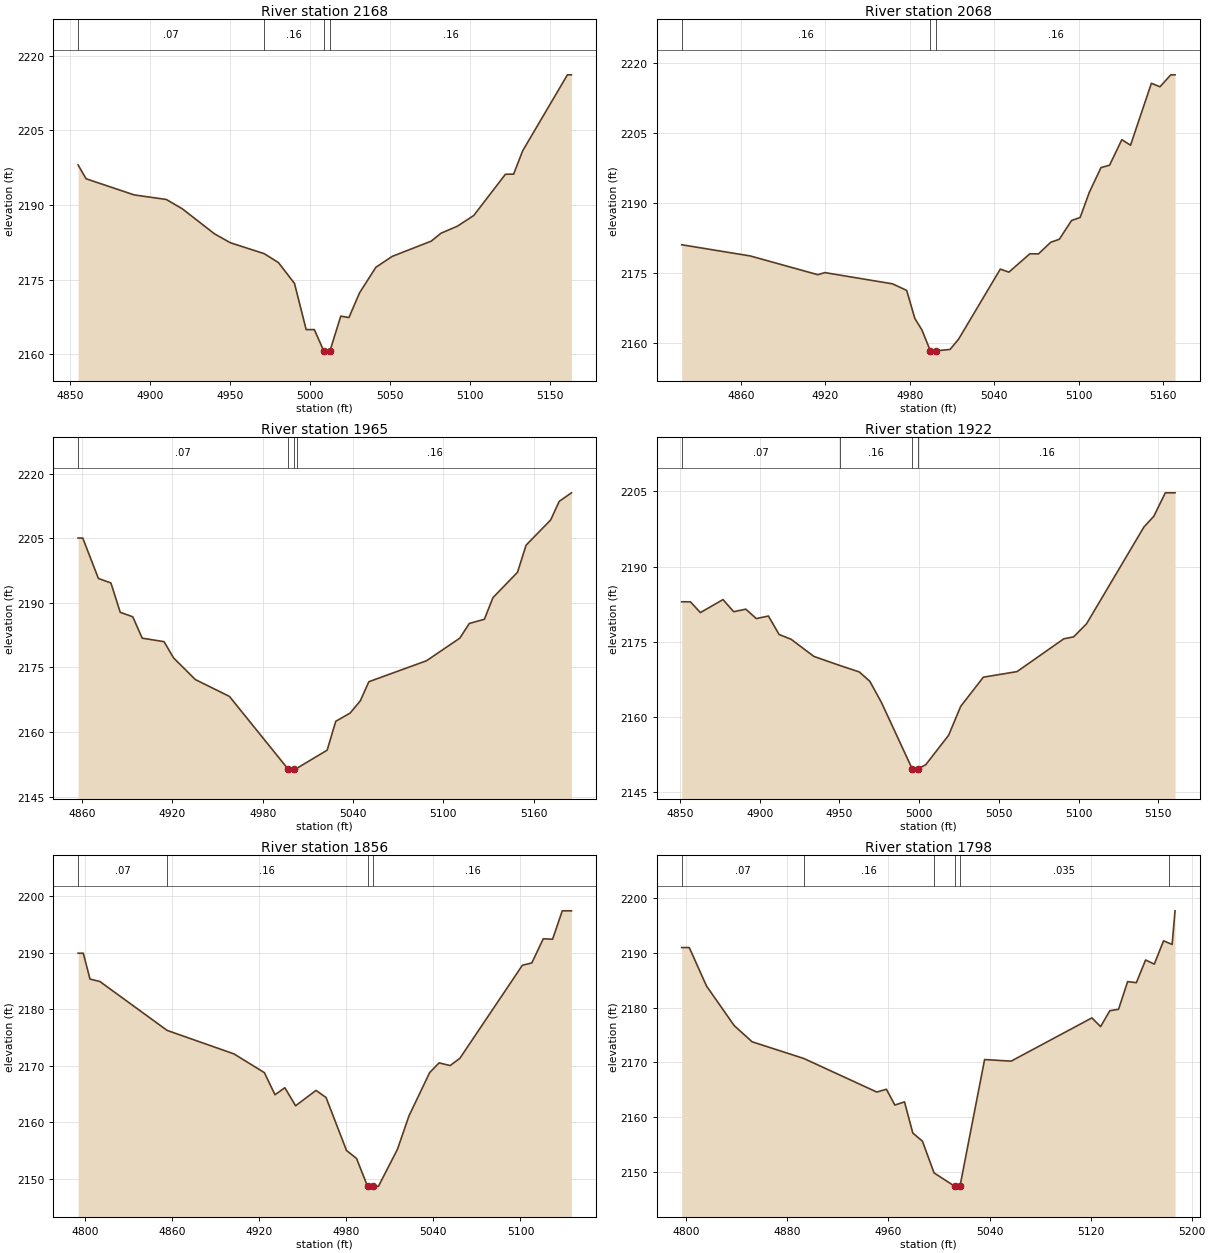
Type RM Length L Ch R = 1,2168,100,100,100
BEGIN DESCRIPTION:
elmc589
END DESCRIPTION:
XS GIS Cut Line= 3
      1511459.97      6773563.05      1511604.71      6773567.39
      1511764.85      6773535.93
#Sta/Elev= 30
  4855.2 2198.06  4860.2 2195.28  4890.2 2192.04  4910.3 2191.12  4920.3 2189.24
  4940.3 2184.23  4950.3 2182.42  4971.4 2180.23  4980.3 2178.43  4990.3 2174.26
  4997.6 2164.97  5002.7 2164.97  5008.5 2160.74  5008.7 2160.24  5012.2 2160.24
  5012.5 2160.74  5019.2 2167.68  5024.3 2167.39  5030.9 2172.34  5041.1 2177.49
  5051.3 2179.68  5075.7 2182.75  5081.8 2184.34  5092.0 2185.75  5102.2 2187.89
  5122.0 2196.19  5127.1 2196.21  5132.8 2200.92  5160.7 2216.17  5163.2 2216.17
#Mann=4,-1,0
  4855.2    0.07       0  4971.4    0.16       0  5008.5    0.07       0
  5012.5    0.16       0
Bank Sta=5008.5,5012.5
Exp/Cntr=0.3,0.1

Type RM Length L Ch R = 1,2068,103,103,103
BEGIN DESCRIPTION:
elmc590
END DESCRIPTION:
XS GIS Cut Line= 3
      1511446.95      6773687.83      1511627.00      6773660.62
      1511764.89      6773564.13
#Sta/Elev= 30
  4817.9 2181.03  4866.5 2178.64  4914.6 2174.62  4919.6 2175.07  4967.6 2172.67
  4977.7 2171.27  4983.5 2165.26  4988.5 2162.82  4994.5 2158.34  4994.7 2157.84
  4998.5 2158.34  5008.5 2158.63  5014.6 2160.84  5044.2 2175.82  5050.3 2175.17
  5065.2 2179.10  5071.3 2179.07  5080.0 2181.56  5086.1 2182.20  5094.8 2186.22
  5100.9 2186.86  5107.4 2192.24  5115.7 2197.53  5121.8 2198.05  5130.5 2203.51
  5136.7 2202.33  5151.5 2215.58  5157.6 2214.84  5165.3 2217.39  5168.3 2217.39
#Mann=3,-1,0
  4817.9    0.16       0  4994.5    0.07       0  4998.5    0.16       0
Bank Sta=4994.5,4998.5
Exp/Cntr=0.3,0.1

Type RM Length L Ch R = 1,1965,43,43,43
BEGIN DESCRIPTION:
elmc403
END DESCRIPTION:
XS GIS Cut Line= 3
      1511555.03      6773837.97      1511668.47      6773751.57
      1511754.98      6773588.04
#Sta/Elev= 30
  4857.4 2205.04  4860.5 2205.04  4870.9 2195.65  4879.2 2194.61  4885.4 2187.79
  4893.7 2186.75  4900.0 2181.78  4914.5 2180.97  4920.8 2177.20  4935.3 2172.16
  4957.9 2168.26  4996.8 2151.40  4997.1 2150.90  5000.8 2151.40  5003.1 2151.65
  5022.8 2155.77  5028.5 2162.47  5038.0 2164.37  5044.8 2167.22  5050.5 2171.67
  5088.8 2176.54  5110.9 2181.79  5117.2 2185.20  5127.2 2186.17  5132.9 2191.20
  5149.2 2197.09  5154.9 2203.39  5171.2 2209.23  5176.9 2213.56  5185.0 2215.54
#Mann=4,-1,0
  4857.4    0.07       0  4996.8    0.07       0  5000.8    0.07       0
  5003.1    0.16       0
Bank Sta=4996.8,5000.8
Exp/Cntr=0.3,0.1

Type RM Length L Ch R = 1,1922,66,66,66
BEGIN DESCRIPTION:
elmc579
END DESCRIPTION:
XS GIS Cut Line= 3
      1511602.78      6773892.36      1511731.26      6773745.44
      1511798.52      6773653.11
#Sta/Elev= 30
  4851.1 2182.99  4856.6 2182.99  4862.8 2180.83  4877.0 2183.43  4883.7 2181.01
  4891.3 2181.52  4897.9 2179.64  4905.5 2180.15  4912.2 2176.47  4919.7 2175.52
  4934.0 2172.10  4950.1 2170.31  4962.5 2169.00  4969.1 2167.14  4976.4 2162.90
  4995.6 2149.73  4995.8 2149.23  4999.6 2149.73  5004.2 2150.52  5018.5 2156.38
  5026.1 2162.16  5040.3 2167.96  5061.4 2169.07  5090.7 2175.60  5096.9 2176.00
  5105.0 2178.60  5141.0 2197.90  5147.2 2200.04  5154.4 2204.71  5160.5 2204.71
#Mann=4,-1,0
  4851.1    0.07       0  4950.1    0.16       0  4995.6    0.07       0
  4999.6    0.16       0
Bank Sta=4995.6,4999.6
Exp/Cntr=0.3,0.1

Type RM Length L Ch R = 1,1856,58,58,58
BEGIN DESCRIPTION:
elmc578
END DESCRIPTION:
XS GIS Cut Line= 3
      1511623.80      6773948.27      1511761.62      6773799.59
      1511848.43      6773693.26
#Sta/Elev= 30
  4795.1 2189.94  4798.7 2189.94  4803.3 2185.37  4810.1 2184.94  4856.5 2176.28
  4902.5 2172.13  4923.5 2168.81  4930.8 2164.90  4937.6 2166.14  4945.0 2162.95
  4959.1 2165.67  4966.0 2164.41  4980.1 2155.04  4987.0 2153.63  4994.6 2148.70
  4994.9 2148.20  4998.6 2148.70  5002.1 2148.70  5015.2 2155.25  5023.1 2161.13
  5037.4 2168.82  5043.9 2170.54  5051.5 2170.06  5058.2 2171.34  5101.3 2187.81
  5107.8 2188.22  5115.7 2192.50  5122.1 2192.41  5128.8 2197.44  5135.1 2197.44
#Mann=4,-1,0
  4795.1    0.07       0  4856.5    0.16       0  4994.6    0.07       0
  4998.6    0.16       0
Bank Sta=4994.6,4998.6
Exp/Cntr=0.3,0.1

Type RM Length L Ch R = 1,1798,54,54,54
BEGIN DESCRIPTION:
elmc577
END DESCRIPTION:
XS GIS Cut Line= 3
      1511650.94      6773972.13      1511801.77      6773840.83
      1511932.58      6773702.45
#Sta/Elev= 30
  4796.4 2190.94  4802.4 2190.94  4816.0 2183.95  4837.9 2176.73  4852.1 2173.77
  4893.0 2170.73  4950.8 2164.61  4958.4 2165.12  4965.1 2162.24  4972.7 2162.82
  4979.3 2157.14  4986.9 2155.66  4996.1 2149.88  5012.6 2147.42  5012.9 2146.92
  5016.6 2147.42  5036.1 2170.53  5057.1 2170.24  5121.0 2178.12  5127.9 2176.53
  5135.2 2179.43  5142.1 2179.69  5149.3 2184.73  5156.2 2184.54  5163.5 2188.67
  5170.4 2187.92  5177.7 2192.16  5181.9 2191.76  5184.5 2191.51  5186.8 2197.63
#Mann=6,-1,0
  4796.4    0.07       0  4893.0    0.16       0  4996.1   0.035       0
  5012.6   0.035       0  5016.6   0.035       0  5181.9    0.07       0
Bank Sta=5012.6,5016.6
Exp/Cntr=0.3,0.1

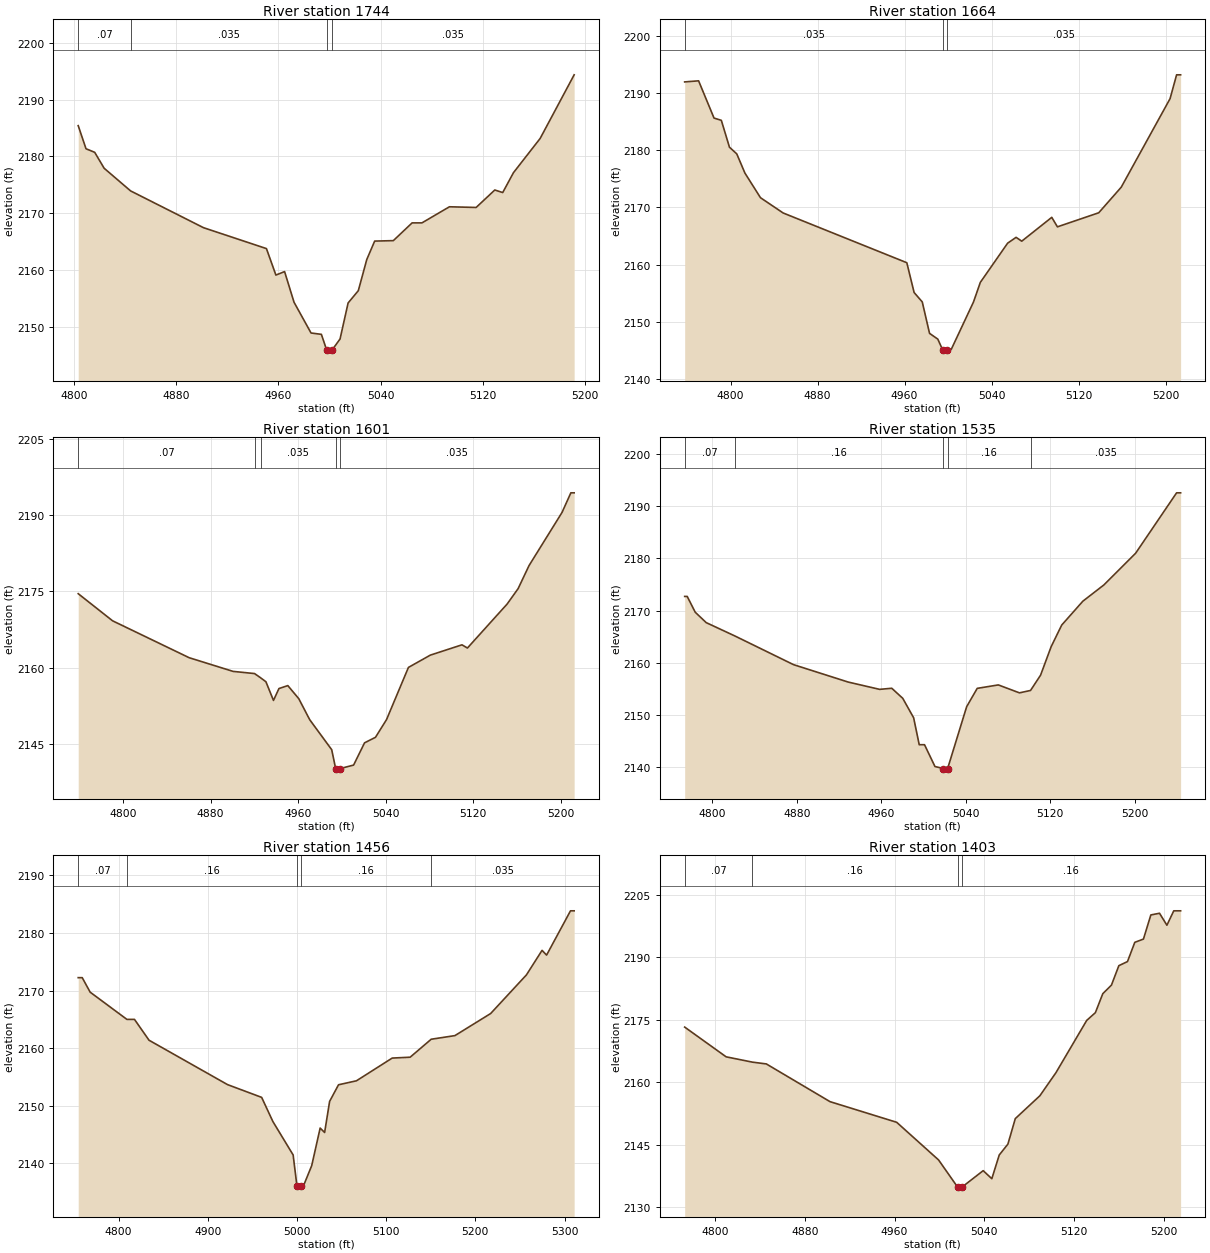
Type RM Length L Ch R = 1,1744,80,80,80
BEGIN DESCRIPTION:
elmc576
END DESCRIPTION:
XS GIS Cut Line= 3
      1511698.71      6774010.08      1511836.49      6773884.23
      1511956.35      6773722.26
#Sta/Elev= 30
  4803.4 2185.42  4809.5 2181.36  4816.3 2180.73  4823.7 2177.93  4844.4 2173.95
  4901.4 2167.49  4950.7 2163.81  4958.1 2159.16  4964.9 2159.77  4972.3 2154.38
  4985.6 2148.98  4993.7 2148.74  4997.9 2145.94  4998.2 2145.44  5001.9 2145.94
  5008.3 2147.92  5014.6 2154.25  5022.6 2156.42  5029.2 2161.88  5035.4 2165.13
  5050.0 2165.21  5064.7 2168.33  5072.4 2168.33  5093.9 2171.16  5114.8 2171.04
  5129.4 2174.11  5135.6 2173.66  5144.0 2177.15  5164.9 2183.17  5191.5 2194.35
#Mann=4,-1,0
  4803.4    0.07       0  4844.4   0.035       0  4997.9   0.035       0
  5001.9   0.035       0
Bank Sta=4997.9,5001.9
Exp/Cntr=0.3,0.1

Type RM Length L Ch R = 1,1664,63,63,63
BEGIN DESCRIPTION:
elmc575
END DESCRIPTION:
XS GIS Cut Line= 3
      1511720.42      6774091.45      1511900.51      6773931.97
      1511963.45      6773725.82
#Sta/Elev= 30
  4757.8 2191.96  4770.6 2192.15  4784.8 2185.63  4791.5 2185.24  4799.0 2180.53
  4805.7 2179.37  4813.2 2176.01  4827.5 2171.70  4848.4 2169.02  4962.1 2160.32
  4968.8 2155.11  4976.3 2153.46  4983.0 2147.96  4990.6 2146.95  4995.2 2145.00
  4995.5 2144.50  4999.2 2145.00  5003.0 2145.17  5023.4 2153.44  5029.7 2156.88
  5054.8 2163.74  5062.6 2164.76  5067.8 2164.09  5095.4 2168.26  5100.6 2166.60
  5138.6 2169.06  5159.3 2173.54  5204.2 2189.03  5210.2 2193.20  5213.9 2193.20
#Mann=3,-1,0
  4757.8   0.035       0  4995.2   0.035       0  4999.2   0.035       0
Bank Sta=4995.2,4999.2
Exp/Cntr=0.3,0.1

Type RM Length L Ch R = 1,1601,66,66,66
BEGIN DESCRIPTION:
elmc574
END DESCRIPTION:
XS GIS Cut Line= 3
      1511952.60      6774179.36      1511962.36      6773941.74
      1511976.47      6773726.92
#Sta/Elev= 30
  4759.0 2174.56  4790.4 2169.22  4860.4 2161.95  4900.5 2159.26  4920.1 2158.83
  4925.7 2157.99  4930.5 2157.22  4937.4 2153.54  4942.4 2155.88  4950.5 2156.46
  4960.5 2153.89  4970.5 2149.75  4990.6 2143.84  4994.2 2140.12  4994.4 2139.62
  4998.2 2140.12  5010.6 2140.81  5020.6 2145.19  5030.6 2146.28  5040.7 2149.77
  5060.7 2160.04  5080.7 2162.46  5109.6 2164.49  5114.6 2163.86  5150.9 2172.53
  5160.9 2175.55  5170.9 2180.10  5201.0 2190.55  5209.1 2194.42  5212.1 2194.42
#Mann=5,-1,0
  4759.0    0.07       0  4920.1    0.16       0  4925.7   0.035       0
  4994.2   0.035       0  4998.2   0.035       0
Bank Sta=4994.2,4998.2
Exp/Cntr=0.3,0.1

Type RM Length L Ch R = 1,1535,79,79,79
BEGIN DESCRIPTION:
elmc573
END DESCRIPTION:
XS GIS Cut Line= 3
      1511972.12      6774157.69      1512028.55      6773942.82
      1512024.21      6773695.42
#Sta/Elev= 30
  4773.9 2172.72  4776.3 2172.72  4783.9 2169.69  4794.3 2167.70  4821.4 2165.15
  4877.0 2159.65  4928.7 2156.32  4958.5 2154.92  4970.0 2155.13  4980.4 2153.20
  4990.7 2149.48  4996.0 2144.32  5001.0 2144.32  5010.9 2140.14  5018.9 2139.76
  5019.1 2139.26  5022.9 2139.76  5040.9 2151.60  5050.9 2155.11  5070.9 2155.77
  5090.9 2154.25  5101.4 2154.71  5110.9 2157.64  5120.9 2163.09  5130.9 2167.23
  5150.9 2171.80  5170.9 2174.93  5200.9 2180.99  5239.7 2192.56  5243.5 2192.56
#Mann=5,-1,0
  4773.9    0.07       0  4821.4    0.16       0  5018.9    0.07       0
  5022.9    0.16       0  5101.4   0.035       0
Bank Sta=5018.9,5022.9
Exp/Cntr=0.3,0.1

Type RM Length L Ch R = 1,1456,53,53,53
BEGIN DESCRIPTION:
elmc572
END DESCRIPTION:
XS GIS Cut Line= 3
      1511991.65      6774160.94      1512107.76      6773941.74
      1512132.71      6773634.71
#Sta/Elev= 30
  4754.7 2172.24  4759.2 2172.24  4768.1 2169.72  4809.3 2164.99  4817.8 2164.99
  4834.1 2161.37  4922.1 2153.66  4960.4 2151.44  4973.0 2147.24  4995.7 2141.44
  5000.0 2136.00  5000.3 2135.50  5004.0 2136.00  5007.1 2136.00  5016.5 2139.57
  5026.0 2146.11  5031.0 2145.34  5036.6 2150.74  5046.6 2153.63  5066.7 2154.32
  5106.8 2158.27  5126.9 2158.42  5150.5 2161.54  5177.1 2162.17  5217.2 2166.01
  5257.3 2172.72  5274.8 2176.98  5279.9 2176.16  5306.7 2183.85  5310.8 2183.85
#Mann=5,-1,0
  4754.7    0.07       0  4809.3    0.16       0  5000.0    0.07       0
  5004.0    0.16       0  5150.5   0.035       0
Bank Sta=5000,5004
Exp/Cntr=0.3,0.1

Type RM Length L Ch R = 1,1403,67,67,67
BEGIN DESCRIPTION:
elmc571
END DESCRIPTION:
XS GIS Cut Line= 3
      1512018.77      6774163.12      1512147.91      6773977.55
      1512287.90      6773813.68
#Sta/Elev= 30
  4773.1 2173.24  4810.0 2166.09  4833.4 2164.81  4845.8 2164.38  4902.5 2155.31
  4961.9 2150.34  4999.2 2141.28  5016.1 2134.77  5016.3 2134.27  5020.1 2134.77
  5038.9 2138.71  5046.6 2136.78  5053.2 2142.48  5060.9 2145.09  5067.5 2151.23
  5089.4 2156.73  5103.7 2162.28  5131.1 2174.85  5138.8 2176.71  5145.4 2181.27
  5153.1 2183.33  5159.7 2188.01  5167.4 2189.00  5173.9 2193.62  5181.6 2194.41
  5188.2 2200.21  5195.9 2200.62  5202.5 2197.74  5208.6 2201.20  5214.7 2201.20
#Mann=4,-1,0
  4773.1    0.07       0  4833.4    0.16       0  5016.1    0.07       0
  5020.1    0.16       0
Bank Sta=5016.1,5020.1
Exp/Cntr=0.3,0.1

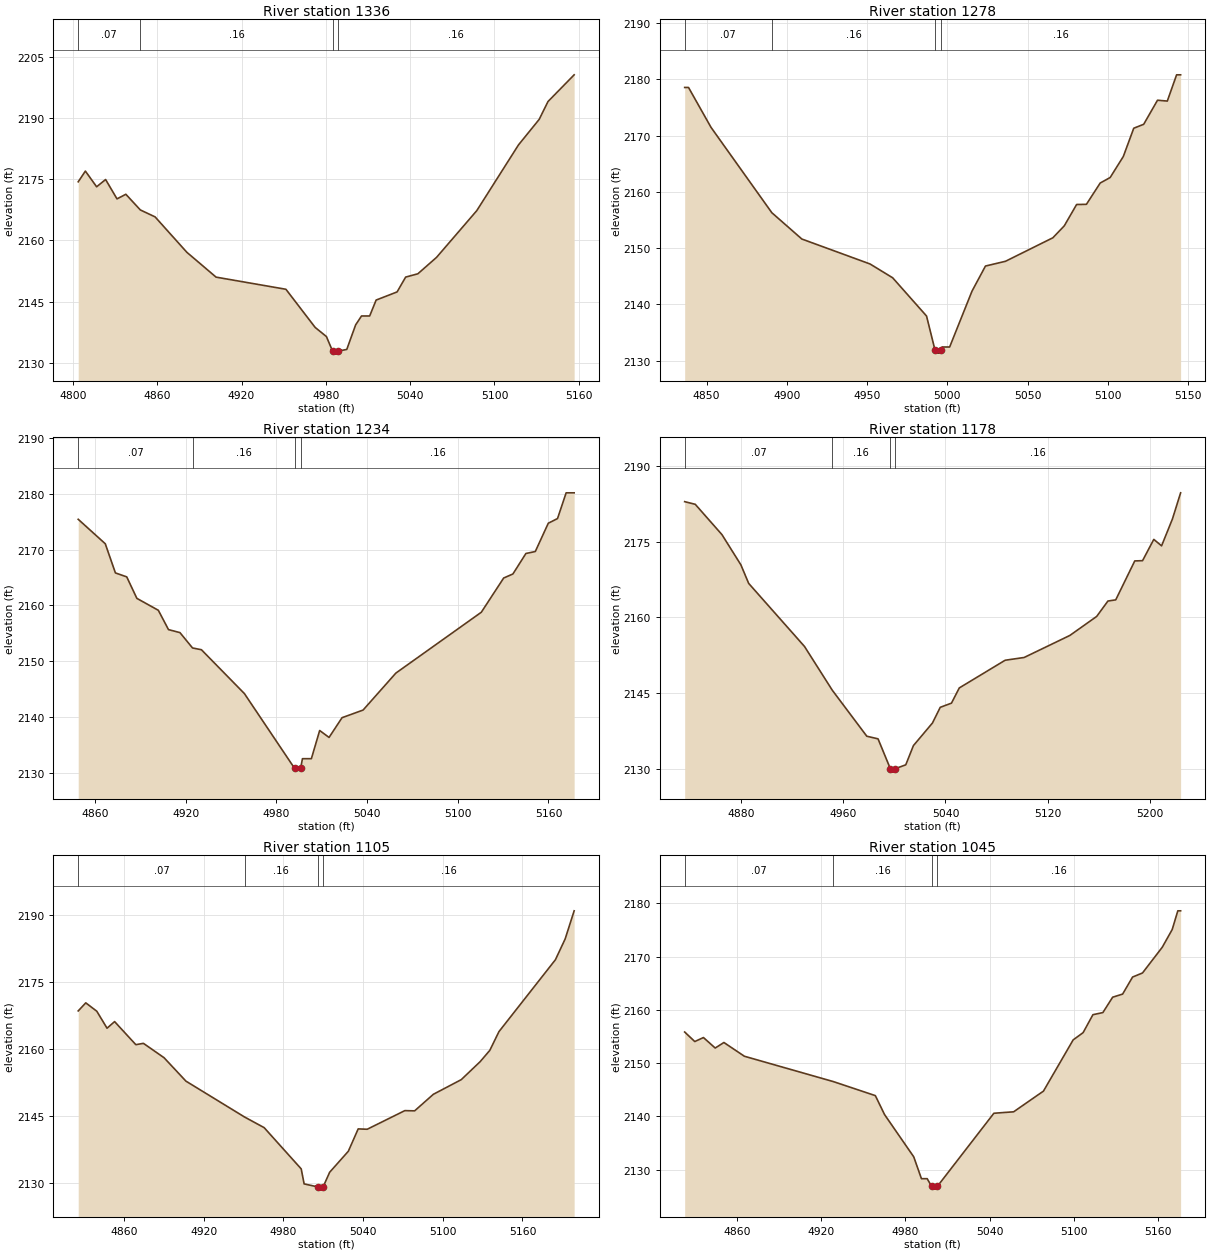
Type RM Length L Ch R = 1,1336,58,58,58
BEGIN DESCRIPTION:
elmc570
END DESCRIPTION:
XS GIS Cut Line= 3
      1512089.32      6774150.07      1512215.18      6773990.57
      1512300.46      6773867.51
#Sta/Elev= 30
  4803.8 2174.35  4808.9 2176.97  4816.9 2173.13  4823.3 2174.91  4831.4 2170.17
  4837.7 2171.30  4848.0 2167.47  4858.5 2165.77  4881.1 2157.11  4901.9 2151.03
  4951.6 2148.06  4972.4 2138.73  4980.4 2136.50  4984.8 2132.94  4985.1 2132.44
  4988.8 2132.94  4994.9 2133.34  5001.2 2139.34  5005.4 2141.53  5011.2 2141.53
  5015.8 2145.42  5030.7 2147.41  5036.8 2151.04  5045.5 2151.85  5058.8 2155.87
  5087.4 2167.29  5117.1 2183.38  5131.8 2189.61  5138.1 2193.99  5156.7 2200.52
#Mann=4,-1,0
  4803.8    0.07       0  4848.0    0.16       0  4984.8    0.07       0
  4988.8    0.16       0
Bank Sta=4984.8,4988.8
Exp/Cntr=0.3,0.1

Type RM Length L Ch R = 1,1278,44,44,44
BEGIN DESCRIPTION:
elmc569
END DESCRIPTION:
XS GIS Cut Line= 3
      1512140.34      6774156.56      1512250.99      6774039.39
      1512336.72      6773918.94
#Sta/Elev= 30
  4836.3 2178.58  4838.7 2178.58  4852.7 2171.49  4890.6 2156.30  4909.3 2151.62
  4951.8 2147.18  4965.9 2144.72  4987.0 2137.92  4992.3 2131.82  4992.5 2131.32
  4996.0 2131.32  4996.3 2131.82  4996.7 2132.41  5001.4 2132.41  5015.3 2142.33
  5023.7 2146.81  5036.2 2147.66  5065.7 2151.84  5072.8 2153.96  5080.5 2157.76
  5086.6 2157.79  5095.2 2161.58  5101.4 2162.56  5109.6 2166.30  5116.1 2171.33
  5122.3 2172.03  5130.9 2176.31  5137.0 2176.16  5142.8 2180.83  5145.3 2180.83
#Mann=4,-1,0
  4836.3    0.07       0  4890.6    0.16       0  4992.3    0.07       0
  4996.3    0.16       0
Bank Sta=4992.3,4996.3
Exp/Cntr=0.3,0.1

Type RM Length L Ch R = 1,1234,56,56,56
BEGIN DESCRIPTION:
elmc568
END DESCRIPTION:
XS GIS Cut Line= 3
      1512170.69      6774168.52      1512283.54      6774068.69
      1512386.62      6773924.39
#Sta/Elev= 30
  4849.0 2175.40  4866.9 2171.03  4873.6 2165.82  4881.1 2165.11  4887.8 2161.27
  4902.0 2159.14  4908.7 2155.69  4916.3 2155.15  4924.6 2152.41  4930.5 2152.09
  4958.9 2144.26  4992.1 2130.90  4992.3 2130.40  4996.1 2130.90  4997.3 2132.62
  5003.2 2132.62  5008.7 2137.66  5014.9 2136.42  5023.5 2139.95  5037.4 2141.31
  5059.1 2147.92  5115.6 2158.79  5130.4 2164.91  5136.5 2165.63  5145.1 2169.29
  5151.3 2169.64  5159.9 2174.70  5166.0 2175.53  5171.7 2180.13  5177.0 2180.13
#Mann=4,-1,0
  4849.0    0.07       0  4924.6    0.16       0  4992.1    0.07       0
  4996.1    0.16       0
Bank Sta=4992.1,4996.1
Exp/Cntr=0.3,0.1

Type RM Length L Ch R = 1,1178,73,73,73
BEGIN DESCRIPTION:
elmc567
END DESCRIPTION:
XS GIS Cut Line= 3
      1512188.04      6774201.08      1512323.69      6774106.67
      1512449.86      6773922.76
#Sta/Elev= 30
  4835.8 2182.95  4844.1 2182.42  4865.0 2176.41  4879.8 2170.43  4885.9 2166.75
  4929.6 2154.25  4951.4 2145.56  4978.4 2136.45  4987.2 2135.93  4996.8 2130.03
  4997.1 2129.53  5000.8 2130.03  5008.9 2130.78  5014.9 2134.59  5029.8 2139.07
  5035.9 2142.18  5044.7 2143.01  5050.8 2146.02  5086.7 2151.51  5101.6 2152.06
  5137.4 2156.43  5158.4 2160.20  5167.2 2163.25  5173.3 2163.48  5188.2 2171.20
  5194.3 2171.25  5203.1 2175.47  5209.2 2174.19  5217.7 2179.52  5224.1 2184.70
#Mann=4,-1,0
  4835.8    0.07       0  4951.4    0.16       0  4996.8    0.07       0
  5000.8    0.16       0
Bank Sta=4996.8,5000.8
Exp/Cntr=0.3,0.1

Type RM Length L Ch R = 1,1105,60,60,60
BEGIN DESCRIPTION:
elmc566
END DESCRIPTION:
XS GIS Cut Line= 3
      1512222.74      6774244.50      1512372.52      6774160.92
      1512520.00      6774023.06
#Sta/Elev= 30
  4825.5 2168.44  4831.2 2170.25  4839.5 2168.37  4847.2 2164.57  4852.9 2166.05
  4868.9 2160.88  4874.6 2161.18  4890.1 2157.97  4906.6 2152.72  4950.7 2144.69
  4965.5 2142.30  4993.4 2133.06  4995.6 2129.70  5005.9 2129.03  5006.2 2128.53
  5009.9 2129.03  5014.8 2132.30  5028.9 2137.02  5036.3 2142.02  5043.1 2141.94
  5071.4 2146.11  5078.8 2146.06  5092.9 2149.77  5113.9 2153.05  5128.1 2157.07
  5135.4 2159.61  5142.3 2163.81  5184.8 2179.91  5192.1 2184.54  5198.9 2190.86
#Mann=4,-1,0
  4825.5    0.07       0  4950.7    0.16       0  5005.9    0.07       0
  5009.9    0.16       0
Bank Sta=5005.9,5009.9
Exp/Cntr=0.3,0.1

Type RM Length L Ch R = 1,1045,64,64,64
BEGIN DESCRIPTION:
elmc565
END DESCRIPTION:
XS GIS Cut Line= 3
      1512275.91      6774308.52      1512412.67      6774206.50
      1512542.88      6774077.37
#Sta/Elev= 30
  4822.4 2155.83  4829.6 2154.04  4835.8 2154.79  4844.2 2152.82  4850.4 2153.86
  4865.0 2151.28  4928.6 2146.51  4958.5 2143.88  4965.1 2140.31  4985.9 2132.39
  4991.4 2128.28  4995.5 2128.28  4998.7 2126.82  4998.9 2126.32  5002.7 2126.82
  5043.1 2140.57  5057.2 2140.84  5078.5 2144.73  5099.7 2154.35  5106.8 2155.71
  5113.8 2159.08  5120.9 2159.48  5127.9 2162.37  5135.0 2162.95  5142.1 2166.15
  5149.2 2166.92  5163.3 2171.75  5170.4 2175.08  5174.4 2178.59  5176.4 2178.59
#Mann=4,-1,0
  4822.4    0.07       0  4928.6    0.16       0  4998.7    0.07       0
  5002.7    0.16       0
Bank Sta=4998.7,5002.7
Exp/Cntr=0.3,0.1

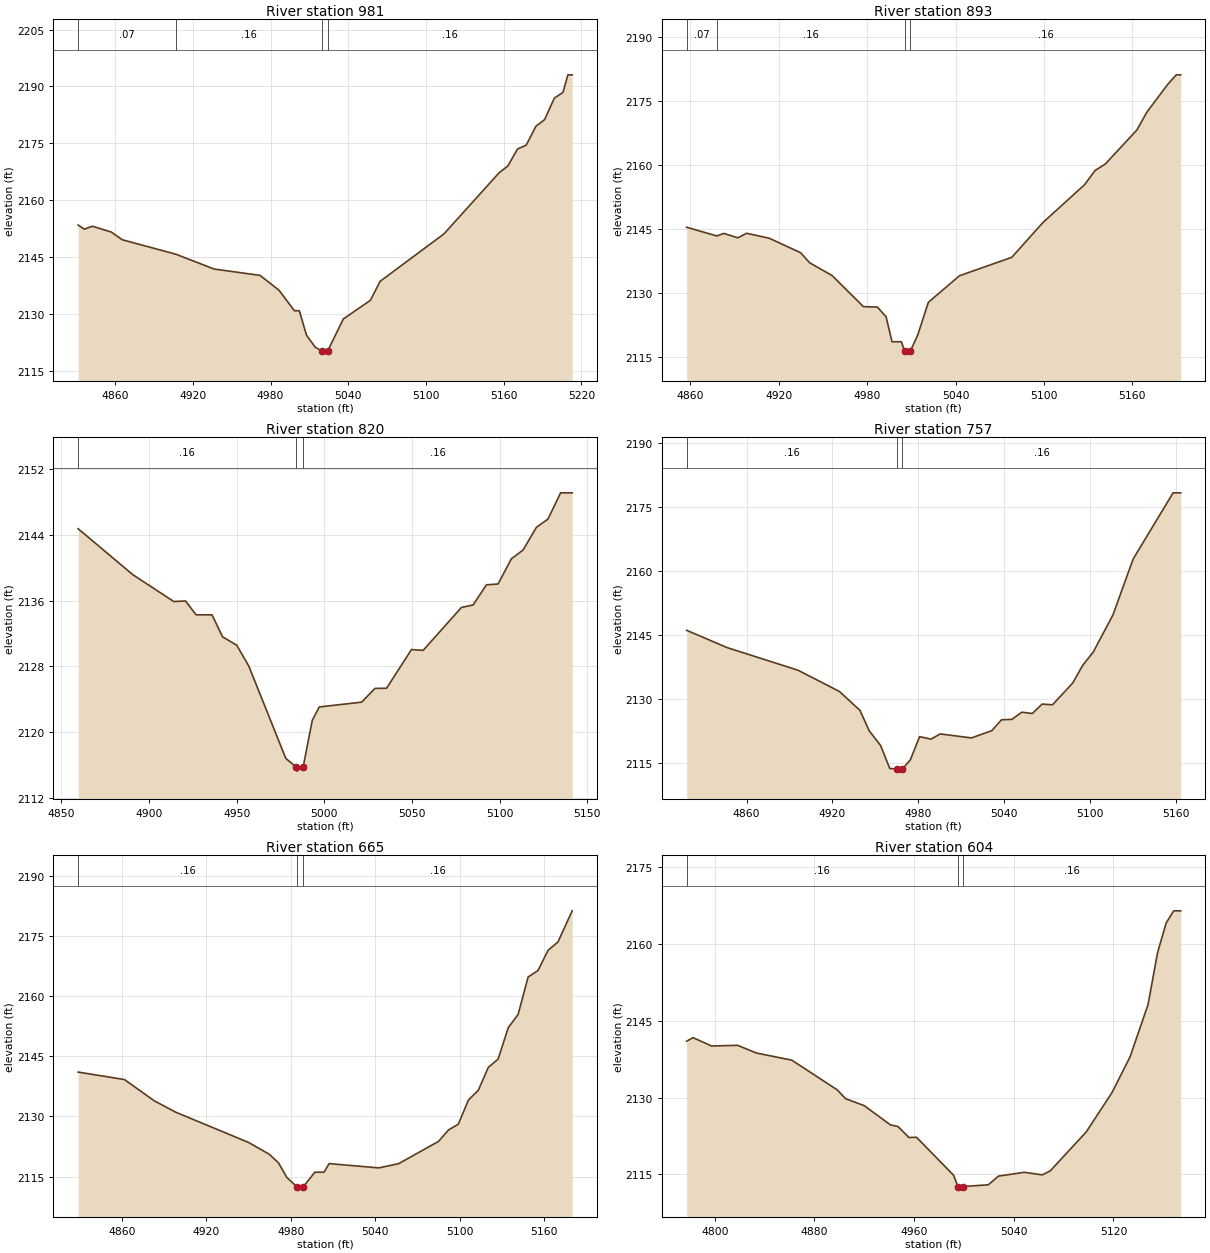
Type RM Length L Ch R = 1,981,88,88,88
BEGIN DESCRIPTION:
elmc402
END DESCRIPTION:
XS GIS Cut Line= 3
      1512326.96      6774346.46      1512462.57      6774246.28
      1512604.98      6774088.02
#Sta/Elev= 30
  4831.4 2153.41  4836.2 2152.31  4842.4 2153.09  4857.0 2151.56  4865.5 2149.52
  4907.0 2145.69  4936.4 2141.79  4971.9 2140.11  4986.5 2136.21  4998.4 2130.78
  5002.2 2130.78  5007.8 2124.30  5014.5 2121.15  5020.0 2120.09  5020.2 2119.59
  5024.0 2120.09  5036.2 2128.61  5057.1 2133.53  5064.6 2138.55  5113.9 2151.07
  5156.5 2167.21  5163.2 2168.98  5170.7 2173.48  5177.4 2174.49  5184.9 2179.49
  5191.6 2181.23  5199.1 2186.89  5205.8 2188.44  5209.6 2193.06  5212.9 2193.06
#Mann=4,-1,0
  4831.4    0.07       0  4907.0    0.16       0  5020.0    0.07       0
  5024.0    0.16       0
Bank Sta=5020,5024
Exp/Cntr=0.3,0.1

Type RM Length L Ch R = 1,893,73,73,73
BEGIN DESCRIPTION:
elmc588
END DESCRIPTION:
XS GIS Cut Line= 3
      1512403.88      6774383.36      1512525.45      6774308.81
      1512664.29      6774175.04
#Sta/Elev= 30
  4857.4 2145.40  4877.8 2143.36  4882.6 2143.95  4892.2 2142.92  4898.1 2143.98
  4913.5 2142.82  4934.8 2139.42  4940.8 2137.09  4956.1 2134.08  4977.4 2126.78
  4986.9 2126.67  4992.8 2124.39  4996.8 2118.54  5003.2 2118.54  5005.3 2116.37
  5005.6 2115.87  5009.3 2116.37  5014.3 2120.15  5021.5 2127.79  5042.6 2134.02
  5078.1 2138.34  5099.2 2146.48  5127.5 2155.37  5134.7 2158.72  5141.6 2160.23
  5163.0 2168.19  5169.9 2172.43  5184.1 2178.96  5189.8 2181.15  5192.8 2181.15
#Mann=4,-1,0
  4857.4    0.07       0  4877.8    0.16       0  5005.3    0.07       0
  5009.3    0.16       0
Bank Sta=5005.3,5009.3
Exp/Cntr=0.3,0.1

Type RM Length L Ch R = 1,820,63,63,63
BEGIN DESCRIPTION:
elmc587
END DESCRIPTION:
XS GIS Cut Line= 3
      1512459.45      6774437.17      1512576.75      6774359.83
      1512669.53      6774253.13
#Sta/Elev= 30
  4859.5 2144.74  4890.7 2139.15  4914.1 2135.88  4920.8 2135.95  4926.8 2134.27
  4935.9 2134.26  4941.9 2131.60  4950.0 2130.57  4956.9 2128.03  4978.0 2116.81
  4983.9 2115.76  4984.2 2115.26  4987.9 2115.76  4993.1 2121.44  4997.1 2123.06
  5021.3 2123.65  5028.9 2125.32  5035.5 2125.34  5049.7 2130.04  5056.4 2129.95
  5078.2 2135.16  5084.9 2135.47  5092.5 2137.92  5099.1 2138.01  5106.7 2141.07
  5113.4 2142.15  5121.0 2144.91  5127.6 2145.91  5134.8 2149.10  5141.4 2149.10
#Mann=3,-1,0
  4859.5    0.16       0  4983.9    0.07       0  4987.9    0.16       0
Bank Sta=4983.9,4987.9
Exp/Cntr=0.3,0.1

Type RM Length L Ch R = 1,757,92,92,92
BEGIN DESCRIPTION:
elmc586
END DESCRIPTION:
XS GIS Cut Line= 3
      1512488.98      6774501.39      1512630.90      6774387.76
      1512749.40      6774275.69
#Sta/Elev= 30
  4818.2 2146.09  4846.4 2142.03  4896.0 2136.70  4924.8 2131.73  4939.2 2127.27
  4945.6 2122.49  4953.6 2119.03  4960.0 2113.62  4964.8 2113.50  4965.1 2113.00
  4968.8 2113.50  4974.4 2115.68  4980.8 2121.10  4988.8 2120.52  4995.2 2121.74
  5017.0 2120.80  5031.2 2122.50  5038.0 2125.06  5045.3 2125.17  5052.2 2126.85
  5059.5 2126.54  5066.4 2128.76  5073.6 2128.59  5087.8 2133.74  5094.7 2137.87
  5102.0 2140.95  5115.8 2149.70  5129.9 2162.84  5157.8 2178.39  5163.1 2178.39
#Mann=3,-1,0
  4818.2    0.16       0  4964.8    0.07       0  4968.8    0.16       0
Bank Sta=4964.8,4968.8
Exp/Cntr=0.3,0.1

Type RM Length L Ch R = 1,665,61,61,61
BEGIN DESCRIPTION:
elmc585
END DESCRIPTION:
XS GIS Cut Line= 3
      1512560.11      6774529.21      1512705.00      6774438.01
      1512830.46      6774309.22
#Sta/Elev= 30
  4828.8 2141.05  4861.7 2139.19  4882.9 2133.89  4898.2 2131.05  4950.0 2123.50
  4964.6 2120.58  4971.2 2118.42  4977.1 2114.80  4984.5 2112.39  4984.7 2111.89
  4988.5 2112.39  4997.0 2116.10  5003.5 2116.10  5007.1 2118.25  5042.4 2117.18
  5056.5 2118.23  5084.8 2123.77  5092.0 2126.64  5098.9 2128.07  5106.1 2134.08
  5113.1 2136.51  5120.2 2142.21  5127.2 2144.30  5134.4 2152.11  5141.4 2155.41
  5148.5 2164.73  5155.5 2166.35  5162.7 2171.40  5169.7 2173.45  5179.8 2181.22
#Mann=3,-1,0
  4828.8    0.16       0  4984.5    0.07       0  4988.5    0.16       0
Bank Sta=4984.5,4988.5
Exp/Cntr=0.3,0.1

Type RM Length L Ch R = 1,604,115,115,115
BEGIN DESCRIPTION:
elmc584
END DESCRIPTION:
XS GIS Cut Line= 3
      1512565.37      6774605.56      1512748.95      6774479.84
      1512856.99      6774343.45
#Sta/Elev= 30
  4777.5 2141.03  4782.6 2141.73  4797.5 2140.10  4818.4 2140.23  4833.4 2138.73
  4861.9 2137.33  4898.3 2131.53  4905.1 2129.80  4920.0 2128.44  4941.0 2124.68
  4947.1 2124.35  4955.9 2122.21  4962.0 2122.25  4991.8 2114.81  4995.2 2112.62
  4995.5 2112.12  4999.2 2112.62  5019.6 2112.97  5027.7 2114.66  5048.5 2115.41
  5062.9 2114.90  5069.3 2115.69  5098.2 2123.31  5119.0 2131.05  5133.4 2138.00
  5147.8 2148.21  5155.4 2158.32  5162.3 2164.13  5168.4 2166.52  5174.0 2166.52
#Mann=3,-1,0
  4777.5    0.16       0  4995.2    0.07       0  4999.2    0.16       0
Bank Sta=4995.2,4999.2
Exp/Cntr=0.3,0.1

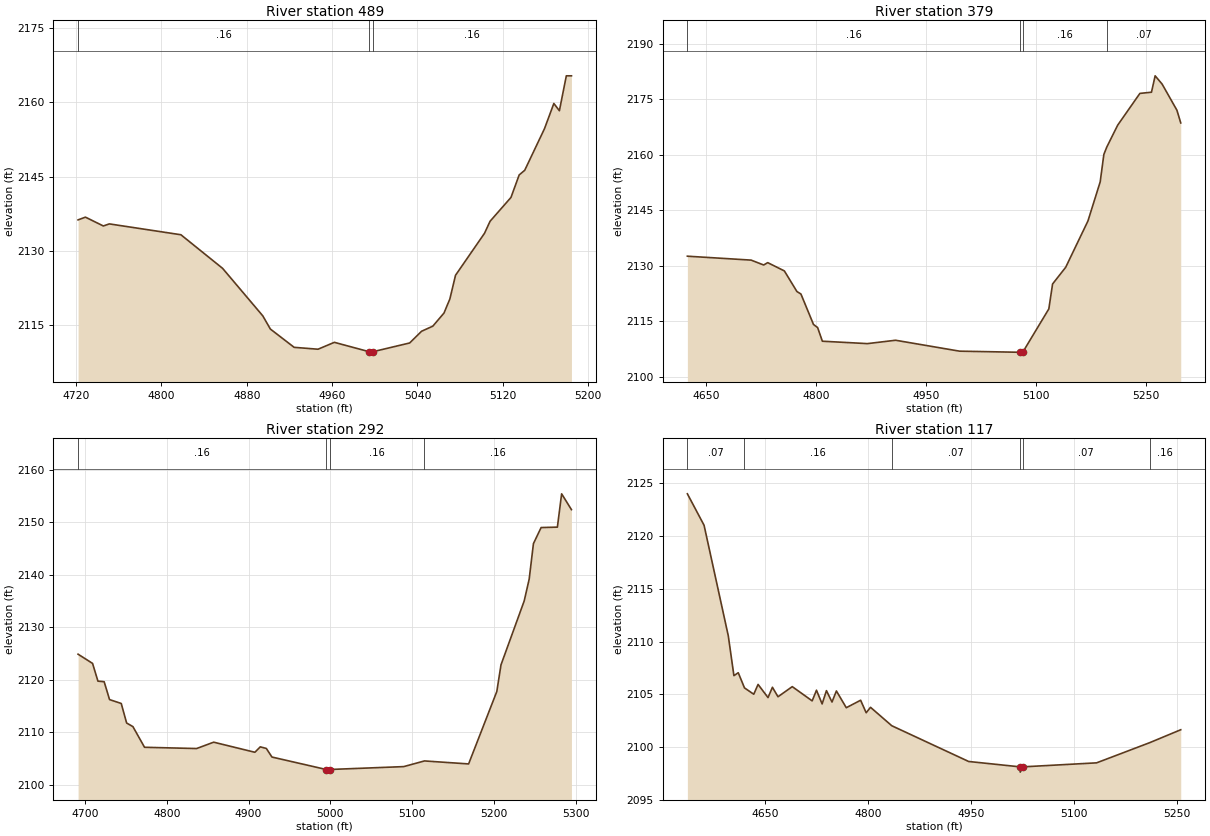
Type RM Length L Ch R = 1,489,110,110,110
BEGIN DESCRIPTION:
elmc583
END DESCRIPTION:
XS GIS Cut Line= 3
      1512600.04      6774654.21      1512848.92      6774529.91
      1512903.87      6774353.88
#Sta/Elev= 30
  4721.8 2136.28  4728.7 2136.83  4745.5 2135.05  4751.1 2135.47  4818.2 2133.28
  4857.3 2126.50  4895.0 2116.91  4902.1 2114.25  4924.4 2110.56  4946.8 2110.18
  4962.1 2111.57  4994.5 2109.69  4994.8 2109.19  4998.5 2109.69  5032.7 2111.44
  5043.9 2113.81  5054.4 2114.83  5064.9 2117.48  5070.4 2120.32  5075.7 2125.10
  5102.9 2133.58  5108.1 2136.00  5127.7 2140.81  5135.4 2145.35  5140.6 2146.29
  5159.1 2154.67  5167.9 2159.77  5173.1 2158.31  5179.6 2165.35  5184.4 2165.35
#Mann=3,-1,0
  4721.8    0.16       0  4994.5    0.07       0  4998.5    0.16       0
Bank Sta=4994.5,4998.5
Exp/Cntr=0.3,0.1

Type RM Length L Ch R = 1,379,87,87,87
BEGIN DESCRIPTION:
elmc582
END DESCRIPTION:
XS GIS Cut Line= 3
      1512619.14      6774699.34      1512957.35      6774537.14
      1512914.31      6774242.87
#Sta/Elev= 30
  4624.9 2132.55  4711.8 2131.49  4728.9 2130.17  4734.4 2130.81  4757.1 2128.57
  4774.2 2123.00  4779.7 2122.32  4796.8 2114.10  4802.4 2113.27  4808.9 2109.57
  4870.3 2108.92  4908.7 2109.83  4995.9 2106.88  5078.0 2106.58  5078.2 2106.08
  5082.0 2106.58  5117.6 2118.31  5122.7 2125.04  5140.6 2129.56  5170.9 2142.07
  5187.6 2152.64  5192.6 2160.06  5196.6 2162.05  5211.4 2167.95  5241.7 2176.55
  5257.5 2176.87  5262.5 2181.30  5272.0 2179.07  5292.2 2172.00  5297.4 2168.57
#Mann=4,-1,0
  4624.9    0.16       0  5078.0    0.07       0  5082.0    0.16       0
  5196.6    0.07       0
Bank Sta=5078,5082
Exp/Cntr=0.3,0.1

Type RM Length L Ch R = 1,292,175,175,175
BEGIN DESCRIPTION:
elmc581
END DESCRIPTION:
XS GIS Cut Line= 3
      1512810.12      6774737.53      1513044.50      6774536.78
      1512966.61      6774252.25
#Sta/Elev= 30
  4691.4 2124.87  4709.1 2123.12  4715.7 2119.74  4723.3 2119.63  4729.9 2116.23
  4744.2 2115.49  4750.8 2111.77  4758.5 2111.08  4772.7 2107.15  4836.4 2106.91
  4857.3 2108.12  4907.7 2106.20  4914.3 2107.23  4921.7 2106.93  4928.6 2105.29
  4995.0 2102.92  4995.3 2102.42  4999.0 2102.92  5089.8 2103.47  5115.2 2104.55
  5169.2 2103.98  5203.7 2117.77  5208.8 2122.84  5237.2 2135.01  5243.3 2139.17
  5248.5 2145.92  5257.9 2148.98  5277.8 2149.06  5283.0 2155.40  5295.0 2152.39
#Mann=4,-1,0
  4691.4    0.16       0  4995.0    0.07       0  4999.0    0.16       0
  5115.2    0.16       0
Bank Sta=4995,4999
Exp/Cntr=0.3,0.1

Type RM Length L Ch R = 1,117,0,0,0
BEGIN DESCRIPTION:
elmc580
END DESCRIPTION:
XS GIS Cut Line= 3
      1512837.94      6774775.70      1513203.47      6774491.52
      1513069.67      6774273.51
#Sta/Elev= 30
  4537.0 2124.02  4561.3 2121.04  4596.6 2110.55  4604.8 2106.77  4611.1 2107.05
  4620.2 2105.61  4633.7 2105.01  4640.0 2105.94  4654.5 2104.69  4660.9 2105.67
  4669.0 2104.77  4689.8 2105.73  4718.8 2104.38  4725.1 2105.39  4733.3 2104.09
  4739.6 2105.35  4747.7 2104.27  4754.1 2105.32  4768.5 2103.73  4789.4 2104.44
  4797.5 2103.25  4803.8 2103.77  4834.8 2102.02  4946.8 2098.63  5021.7 2098.12
  5022.0 2097.62  5025.7 2098.12  5133.2 2098.50  5210.4 2100.41  5255.8 2101.64
#Mann=6,-1,0
  4537.0    0.07       0  4620.2    0.16       0  4834.8    0.07       0
  5021.7    0.07       0  5025.7    0.07       0  5210.4    0.16       0
Bank Sta=5021.7,5025.7
Exp/Cntr=0.3,0.1

Chan Stop Cuts=-1