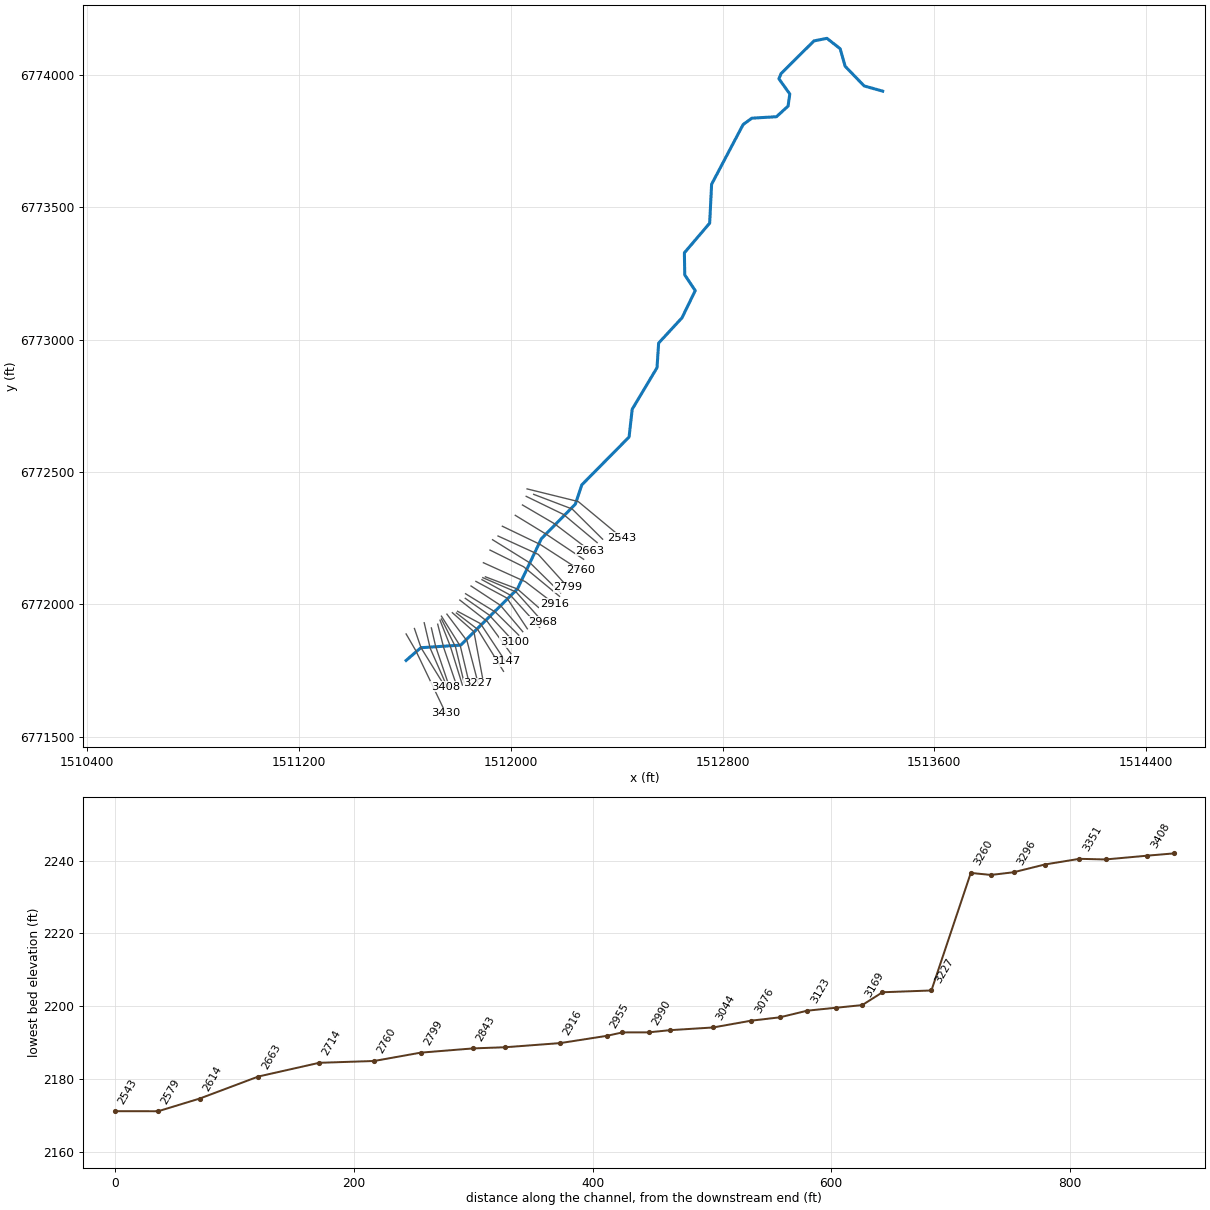
--- Elm 46.prj (project) ---

Proj Title=Elm 46 Base Level Engineering
Current Plan=p01
Default Exp/Contr=0.3,0.1
English Units
Geom File=g01
Flow File=f01
Plan File=p01
BEGIN DESCRIPTION:
Elm 46
END DESCRIPTION:

--- Elm 46.p01 (plan) ---

Plan Title=Multiple Run
Short Identifier=Multiple
Geom File=g01
Flow File=f01
Subcritical Flow
K Sum by GR= 0
Std Step Tol= 0.01
Critical Tol= 0.01
Num of Std Step Trials= 20
Max Error Tol= 0.3
Flow Tol Ratio= 0.001
Split Flow NTrial= 30
Split Flow Tol= 0.02
Split Flow Ratio= 0.02
Log Output Level= 0
Friction Slope Method= 1
Unsteady Friction Slope Method= 2
Unsteady Bridges Friction Slope Method= 1
Parabolic Critical Depth
Global Vel Dist=  1 , 1 , 1
Global Log Level= 0
CheckData=True
Encroach Param= -1, 0, 0, 0
BEGIN DESCRIPTION:
Multiple Run
END DESCRIPTION:

--- Elm 46.f01 (steady flow) ---

Flow Title=Multiple
Number of Profiles=7
Profile Names=10-year,25-year,50-year,1pct_min,100-year,1pct_plu,500-year
River Rch & RM= Elm 46,Reach-1,3430
     151     207     255     195     313     430     476
Boundary for River Rch & Prof#=Elm 46,Reach-1,1
Up Type=0
Dn Type=3
Dn Slope=0.005
Boundary for River Rch & Prof#=Elm 46,Reach-1,2
Up Type=0
Dn Type=3
Dn Slope=0.005
Boundary for River Rch & Prof#=Elm 46,Reach-1,3
Up Type=0
Dn Type=3
Dn Slope=0.005
Boundary for River Rch & Prof#=Elm 46,Reach-1,4
Up Type=0
Dn Type=3
Dn Slope=0.005
Boundary for River Rch & Prof#=Elm 46,Reach-1,5
Up Type=0
Dn Type=3
Dn Slope=0.005
Boundary for River Rch & Prof#=Elm 46,Reach-1,6
Up Type=0
Dn Type=3
Dn Slope=0.005
Boundary for River Rch & Prof#=Elm 46,Reach-1,7
Up Type=0
Dn Type=3
Dn Slope=0.005

--- Elm 46.g01 (geometry) ---

Geom Title=Existing Conditions

River Reach=Elm 46,Reach-1
Reach XY= 30
      1511605.00      6771788.00      1511660.79      6771836.09
      1511811.19      6771845.81      1512025.39      6772057.84
      1512115.77      6772247.68      1512244.22      6772378.32
      1512268.63      6772451.21      1512447.14      6772631.83
      1512458.83      6772736.41      1512552.67      6772893.97
      1512558.62      6772986.50      1512646.86      6773081.96
      1512696.96      6773184.68      1512657.36      6773243.90
      1512655.95      6773327.51      1512751.44      6773439.47
      1512758.76      6773586.44      1512877.81      6773811.95
      1512910.71      6773835.92      1513003.78      6773841.53
      1513047.63      6773881.63      1513054.13      6773927.31
      1513012.91      6773984.77      1513021.30      6774004.70
      1513145.34      6774127.83      1513194.51      6774137.52
      1513244.35      6774098.11      1513263.15      6774031.96
      1513334.86      6773957.76      1513405.00      6773938.00

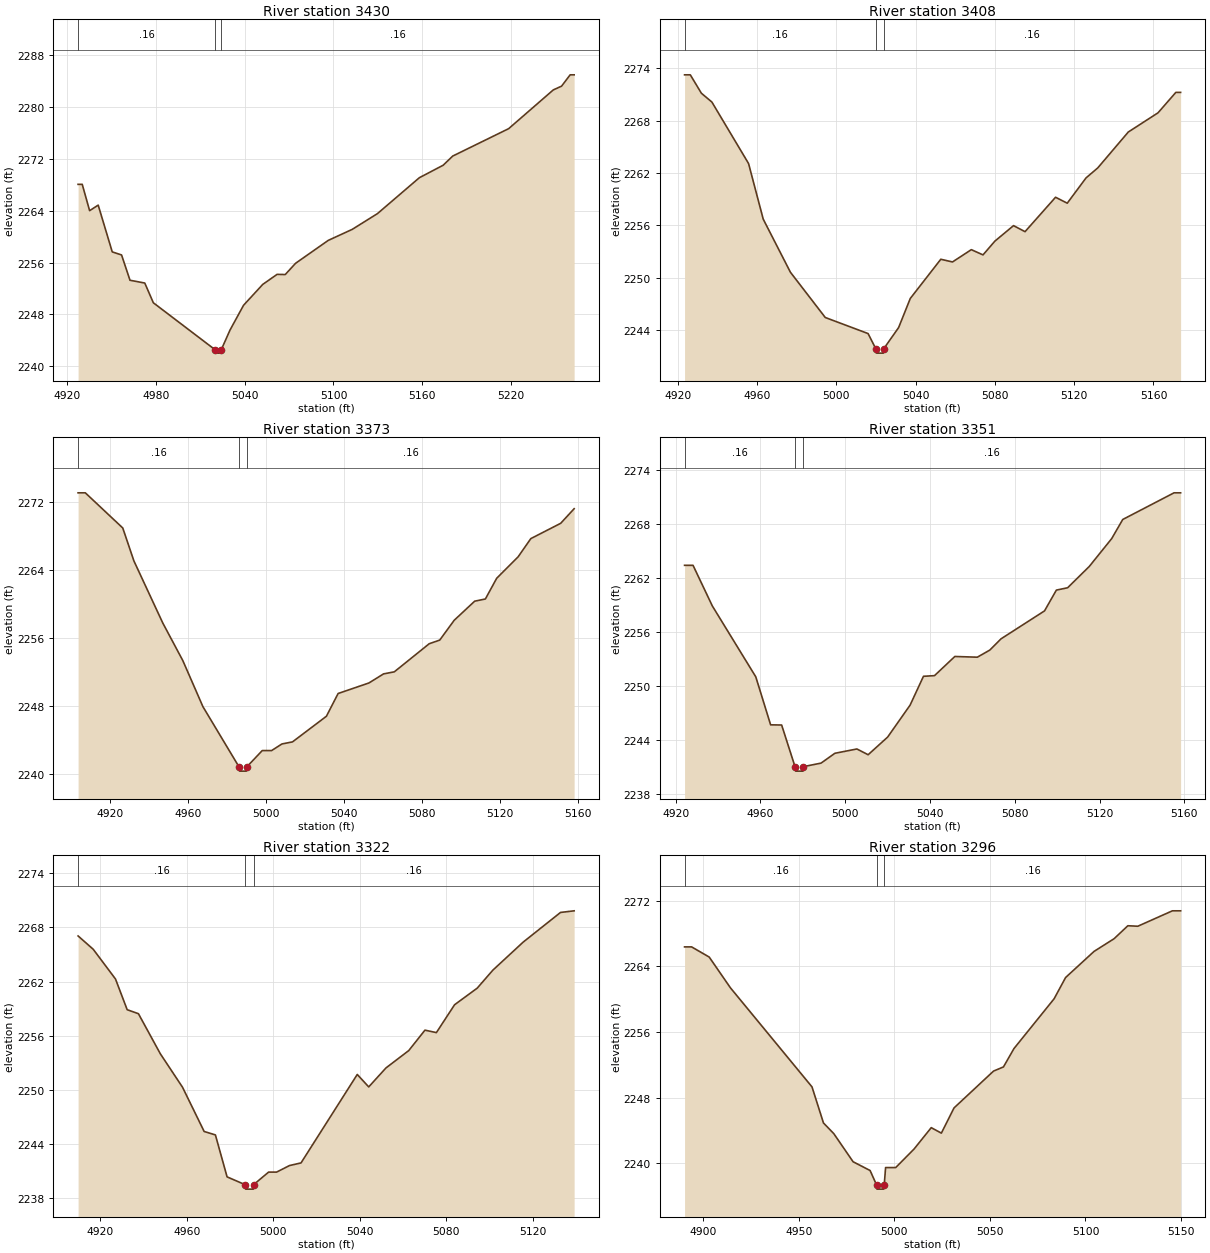
Type RM Length L Ch R = 1,3430,22,22,22
BEGIN DESCRIPTION:
elmc399
END DESCRIPTION:
XS GIS Cut Line= 3
      1511605.02      6771887.96      1511641.50      6771825.08
      1511754.98      6771588.04
#Sta/Elev= 30
  4927.3 2268.08  4930.1 2268.08  4935.1 2264.01  4940.9 2264.87  4950.4 2257.64
  4956.7 2257.17  4962.4 2253.26  4972.4 2252.83  4978.2 2249.78  5020.1 2242.50
  5020.3 2242.00  5023.8 2242.00  5024.1 2242.50  5030.0 2245.54  5039.2 2249.39
  5052.2 2252.62  5061.9 2254.17  5067.4 2254.14  5074.4 2255.88  5096.5 2259.42
  5112.7 2261.12  5129.8 2263.56  5158.1 2269.10  5174.2 2271.03  5180.7 2272.45
  5218.5 2276.68  5248.7 2282.67  5254.3 2283.25  5260.1 2285.00  5262.8 2285.00
#Mann=3,-1,0
  4927.3    0.16       0  5020.1    0.07       0  5024.1    0.16       0
Bank Sta=5020.1,5024.1
Exp/Cntr=0.3,0.1

Type RM Length L Ch R = 1,3408,35,35,35
BEGIN DESCRIPTION:
elmc554
END DESCRIPTION:
XS GIS Cut Line= 3
      1511636.40      6771908.55      1511661.36      6771835.84
      1511752.50      6771688.29
#Sta/Elev= 30
  4923.4 2273.25  4926.3 2273.25  4931.9 2271.14  4937.2 2270.13  4955.7 2263.09
  4963.1 2256.72  4976.8 2250.65  4994.4 2245.46  5016.0 2243.62  5019.9 2241.88
  5020.2 2241.38  5023.7 2241.38  5023.9 2241.88  5031.4 2244.30  5037.3 2247.64
  5052.7 2252.13  5058.6 2251.82  5068.1 2253.23  5074.0 2252.63  5080.0 2254.21
  5089.4 2255.98  5095.2 2255.29  5110.6 2259.23  5116.5 2258.55  5126.0 2261.45
  5131.9 2262.59  5147.3 2266.70  5162.3 2268.90  5171.3 2271.24  5173.7 2271.24
#Mann=3,-1,0
  4923.4    0.16       0  5019.9    0.07       0  5023.9    0.16       0
Bank Sta=5019.9,5023.9
Exp/Cntr=0.3,0.1

Type RM Length L Ch R = 1,3373,22,22,22
BEGIN DESCRIPTION:
elmc557
END DESCRIPTION:
XS GIS Cut Line= 3
      1511673.30      6771930.25      1511696.09      6771833.67
      1511758.47      6771691.70
#Sta/Elev= 30
  4903.8 2273.11  4907.5 2273.11  4926.7 2268.97  4932.4 2265.10  4947.2 2257.79
  4957.5 2253.35  4967.8 2247.93  4986.3 2240.84  4986.6 2240.34  4990.1 2240.34
  4990.3 2240.84  4998.2 2242.76  5003.0 2242.76  5008.3 2243.54  5013.7 2243.78
  5031.1 2246.80  5037.1 2249.48  5052.9 2250.72  5060.4 2251.79  5065.9 2252.03
  5083.8 2255.34  5089.2 2255.77  5096.6 2258.10  5107.1 2260.35  5112.6 2260.61
  5118.4 2263.05  5129.4 2265.58  5135.9 2267.72  5151.2 2269.52  5158.1 2271.24
#Mann=3,-1,0
  4903.8    0.16       0  4986.3    0.07       0  4990.3    0.16       0
Bank Sta=4986.3,4990.3
Exp/Cntr=0.3,0.1

Type RM Length L Ch R = 1,3351,29,29,29
BEGIN DESCRIPTION:
elmc555
END DESCRIPTION:
XS GIS Cut Line= 3
      1511700.42      6771910.72      1511716.70      6771840.18
      1511768.78      6771687.19
#Sta/Elev= 30
  4924.2 2263.36  4928.2 2263.36  4937.3 2258.85  4957.8 2250.98  4964.8 2245.65
  4970.0 2245.63  4976.3 2241.01  4976.6 2240.51  4980.1 2240.51  4980.3 2241.01
  4988.6 2241.40  4995.1 2242.49  5005.5 2242.97  5010.8 2242.33  5020.0 2244.29
  5030.6 2247.84  5036.9 2251.04  5042.1 2251.11  5051.7 2253.24  5062.3 2253.16
  5068.2 2253.95  5073.5 2255.20  5094.0 2258.30  5099.6 2260.61  5104.9 2260.87
  5115.1 2263.23  5125.7 2266.33  5130.9 2268.45  5155.1 2271.41  5158.2 2271.41
#Mann=3,-1,0
  4924.2    0.16       0  4976.3    0.07       0  4980.3    0.16       0
Bank Sta=4976.3,4980.3
Exp/Cntr=0.3,0.1

Type RM Length L Ch R = 1,3322,26,26,26
BEGIN DESCRIPTION:
elmc558
END DESCRIPTION:
XS GIS Cut Line= 3
      1511724.31      6771924.77      1511747.08      6771835.84
      1511791.57      6771705.63
#Sta/Elev= 30
  4909.8 2267.06  4916.8 2265.58  4927.1 2262.28  4932.5 2258.87  4937.7 2258.43
  4947.8 2253.99  4958.1 2250.26  4968.1 2245.35  4973.3 2244.97  4978.7 2240.31
  4987.0 2239.45  4987.3 2238.95  4990.8 2238.95  4991.0 2239.45  4997.9 2240.84
  5001.6 2240.84  5007.6 2241.57  5012.9 2241.86  5038.9 2251.68  5044.2 2250.30
  5052.2 2252.41  5062.7 2254.33  5070.2 2256.60  5075.5 2256.33  5083.9 2259.42
  5094.4 2261.27  5101.6 2263.26  5115.6 2266.37  5132.9 2269.67  5139.2 2269.85
#Mann=3,-1,0
  4909.8    0.16       0  4987.0    0.07       0  4991.0    0.16       0
Bank Sta=4987,4991
Exp/Cntr=0.3,0.1

Type RM Length L Ch R = 1,3296,19,19,19
BEGIN DESCRIPTION:
elmc559
END DESCRIPTION:
XS GIS Cut Line= 3
      1511732.99      6771939.98      1511772.04      6771841.26
      1511817.62      6771694.75
#Sta/Elev= 30
  4890.2 2266.38  4893.9 2266.38  4903.1 2265.14  4914.2 2261.39  4956.9 2249.30
  4962.9 2244.90  4968.3 2243.60  4978.4 2240.17  4987.3 2239.10  4990.7 2237.33
  4990.9 2236.83  4994.4 2236.83  4994.7 2237.33  4995.4 2239.46  5000.7 2239.46
  5010.3 2241.72  5019.3 2244.33  5024.6 2243.66  5031.2 2246.73  5051.9 2251.23
  5057.1 2251.74  5062.6 2253.98  5083.6 2260.05  5089.6 2262.64  5104.5 2265.83
  5115.0 2267.38  5122.2 2268.96  5127.4 2268.90  5145.5 2270.78  5149.8 2270.78
#Mann=3,-1,0
  4890.2    0.16       0  4990.7    0.07       0  4994.7    0.16       0
Bank Sta=4990.7,4994.7
Exp/Cntr=0.3,0.1

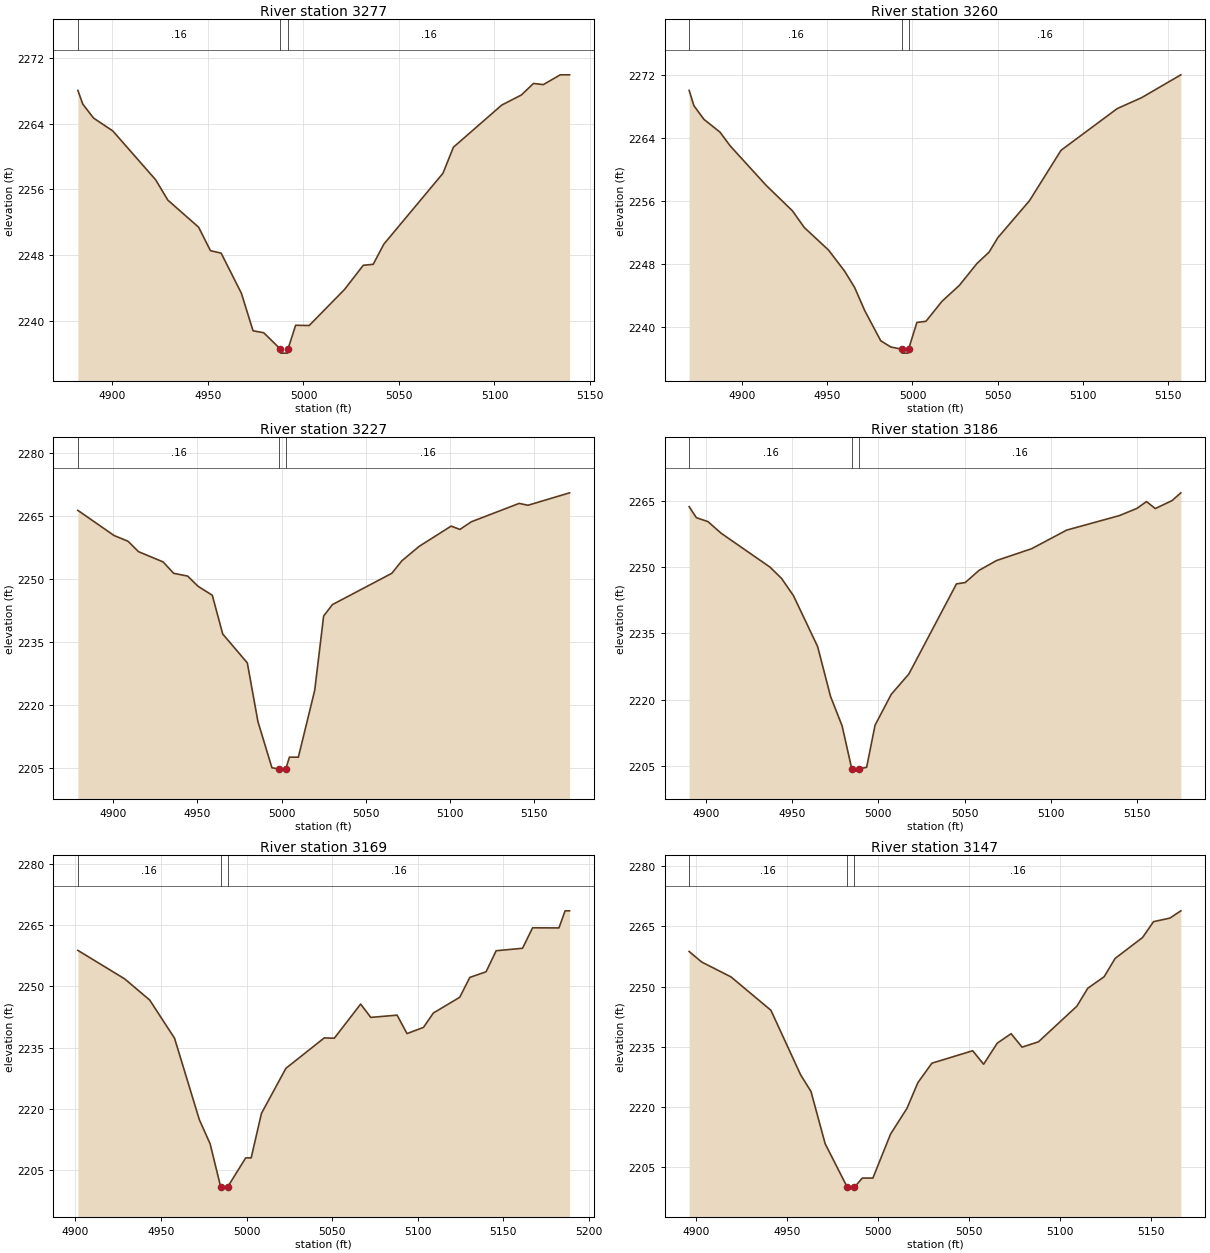
Type RM Length L Ch R = 1,3277,17,17,17
BEGIN DESCRIPTION:
elmc560
END DESCRIPTION:
XS GIS Cut Line= 3
      1511738.39      6771944.37      1511791.57      6771839.09
      1511824.12      6771703.49
#Sta/Elev= 30
  4881.9 2268.05  4884.5 2266.38  4890.1 2264.69  4900.2 2263.12  4922.6 2257.18
  4929.0 2254.70  4945.1 2251.41  4951.3 2248.55  4956.9 2248.25  4967.5 2243.37
  4973.6 2238.80  4979.2 2238.56  4987.9 2236.58  4988.1 2236.08  4991.6 2236.08
  4991.9 2236.58  4995.9 2239.47  5003.0 2239.44  5021.5 2243.83  5031.3 2246.77
  5036.5 2246.89  5042.1 2249.35  5073.0 2257.96  5078.5 2261.14  5103.8 2266.27
  5114.1 2267.50  5120.4 2268.90  5125.6 2268.76  5134.4 2269.95  5139.3 2269.95
#Mann=3,-1,0
  4881.9    0.16       0  4987.9    0.07       0  4991.9    0.16       0
Bank Sta=4987.9,4991.9
Exp/Cntr=0.3,0.1

Type RM Length L Ch R = 1,3260,33,33,33
BEGIN DESCRIPTION:
elmc556
END DESCRIPTION:
XS GIS Cut Line= 3
      1511738.43      6771955.16      1511810.02      6771841.26
      1511845.52      6771691.74
#Sta/Elev= 30
  4869.1 2269.99  4871.9 2268.05  4877.8 2266.31  4887.2 2264.69  4893.1 2262.96
  4914.3 2257.92  4929.6 2254.71  4936.6 2252.58  4950.8 2249.72  4960.2 2247.05
  4966.1 2244.97  4972.0 2242.04  4981.4 2238.20  4987.3 2237.41  4993.7 2237.13
  4993.9 2236.63  4997.4 2236.63  4997.7 2237.13  5002.6 2240.53  5007.9 2240.67
  5017.3 2243.21  5027.5 2245.24  5037.8 2248.01  5044.9 2249.45  5050.0 2251.28
  5068.6 2255.99  5087.1 2262.39  5120.0 2267.68  5134.4 2269.08  5157.3 2271.97
#Mann=3,-1,0
  4869.1    0.16       0  4993.7    0.07       0  4997.7    0.16       0
Bank Sta=4993.7,4997.7
Exp/Cntr=0.3,0.1

Type RM Length L Ch R = 1,3227,41,41,41
BEGIN DESCRIPTION:
elmc561
END DESCRIPTION:
XS GIS Cut Line= 3
      1511759.04      6771962.76      1511834.98      6771861.88
      1511876.92      6771701.64
#Sta/Elev= 30
  4879.1 2266.33  4900.6 2260.35  4908.9 2258.98  4915.1 2256.51  4929.7 2254.07
  4936.0 2251.36  4944.3 2250.70  4950.5 2248.26  4958.9 2246.15  4965.1 2236.93
  4979.7 2230.06  4986.0 2216.10  4994.3 2205.14  4998.5 2204.83  4998.8 2204.33
  5002.5 2204.83  5004.7 2207.65  5010.0 2207.65  5019.7 2223.53  5025.0 2241.20
  5030.2 2243.92  5065.5 2251.37  5071.4 2254.32  5081.7 2257.77  5100.7 2262.59
  5105.9 2261.80  5112.7 2263.62  5141.1 2267.99  5146.3 2267.54  5171.0 2270.50
#Mann=3,-1,0
  4879.1    0.16       0  4998.5    0.07       0  5002.5    0.16       0
Bank Sta=4998.5,5002.5
Exp/Cntr=0.3,0.1

Type RM Length L Ch R = 1,3186,17,17,17
BEGIN DESCRIPTION:
elmc562
END DESCRIPTION:
XS GIS Cut Line= 3
      1511779.61      6771968.24      1511861.02      6771896.60
      1511893.57      6771722.97
#Sta/Elev= 30
  4890.3 2263.70  4894.5 2261.20  4901.2 2260.32  4908.8 2257.70  4937.2 2250.01
  4943.9 2247.45  4950.8 2243.55  4964.8 2232.03  4972.3 2220.74  4979.0 2214.08
  4984.6 2204.34  4984.8 2203.84  4988.3 2203.84  4988.6 2204.34  4993.2 2204.69
  4998.1 2214.24  5007.5 2221.23  5017.7 2225.82  5045.3 2246.22  5050.4 2246.53
  5058.4 2249.28  5068.5 2251.50  5088.9 2254.18  5109.2 2258.39  5139.8 2261.68
  5149.9 2263.30  5155.5 2264.85  5160.6 2263.27  5170.3 2265.07  5175.4 2266.83
#Mann=3,-1,0
  4890.3    0.16       0  4984.6    0.07       0  4988.6    0.16       0
Bank Sta=4984.6,4988.6
Exp/Cntr=0.3,0.1

Type RM Length L Ch R = 1,3169,22,22,22
BEGIN DESCRIPTION:
elmc564
END DESCRIPTION:
XS GIS Cut Line= 3
      1511794.84      6771967.12      1511875.12      6771905.28
      1511972.76      6771746.89
#Sta/Elev= 30
  4901.4 2258.83  4928.8 2251.83  4943.4 2246.65  4957.9 2237.30  4972.4 2217.33
  4978.7 2211.42  4984.9 2200.81  4985.1 2200.31  4988.9 2200.81  4999.5 2207.97
  5002.7 2207.97  5008.7 2218.87  5023.0 2229.92  5045.4 2237.37  5051.3 2237.30
  5066.7 2245.67  5072.6 2242.40  5088.0 2242.95  5093.8 2238.43  5103.4 2239.95
  5109.2 2243.48  5124.6 2247.33  5130.5 2252.20  5140.0 2253.58  5145.9 2258.74
  5161.3 2259.34  5167.2 2264.36  5182.6 2264.33  5186.2 2268.52  5188.8 2268.52
#Mann=3,-1,0
  4901.4    0.16       0  4984.9    0.07       0  4988.9    0.16       0
Bank Sta=4984.9,4988.9
Exp/Cntr=0.3,0.1

Type RM Length L Ch R = 1,3147,24,24,24
BEGIN DESCRIPTION:
elmc563
END DESCRIPTION:
XS GIS Cut Line= 3
      1511799.19      6771973.63      1511885.97      6771926.98
      1511980.59      6771783.97
#Sta/Elev= 30
  4896.3 2258.78  4903.1 2256.17  4919.3 2252.44  4941.2 2244.13  4957.5 2228.07
  4963.2 2223.91  4971.0 2210.88  4983.1 2200.08  4983.3 2199.58  4987.1 2200.08
  4991.4 2202.33  4997.2 2202.33  5006.9 2213.29  5015.9 2219.69  5021.9 2226.10
  5029.6 2230.95  5052.0 2234.05  5058.0 2230.69  5065.5 2235.94  5073.1 2238.30
  5079.1 2234.95  5088.1 2236.27  5109.2 2245.14  5115.2 2249.61  5124.2 2252.49
  5130.2 2257.04  5145.3 2262.26  5151.3 2266.20  5160.3 2267.09  5166.3 2268.90
#Mann=3,-1,0
  4896.3    0.16       0  4983.1    0.07       0  4987.1    0.16       0
Bank Sta=4983.1,4987.1
Exp/Cntr=0.3,0.1

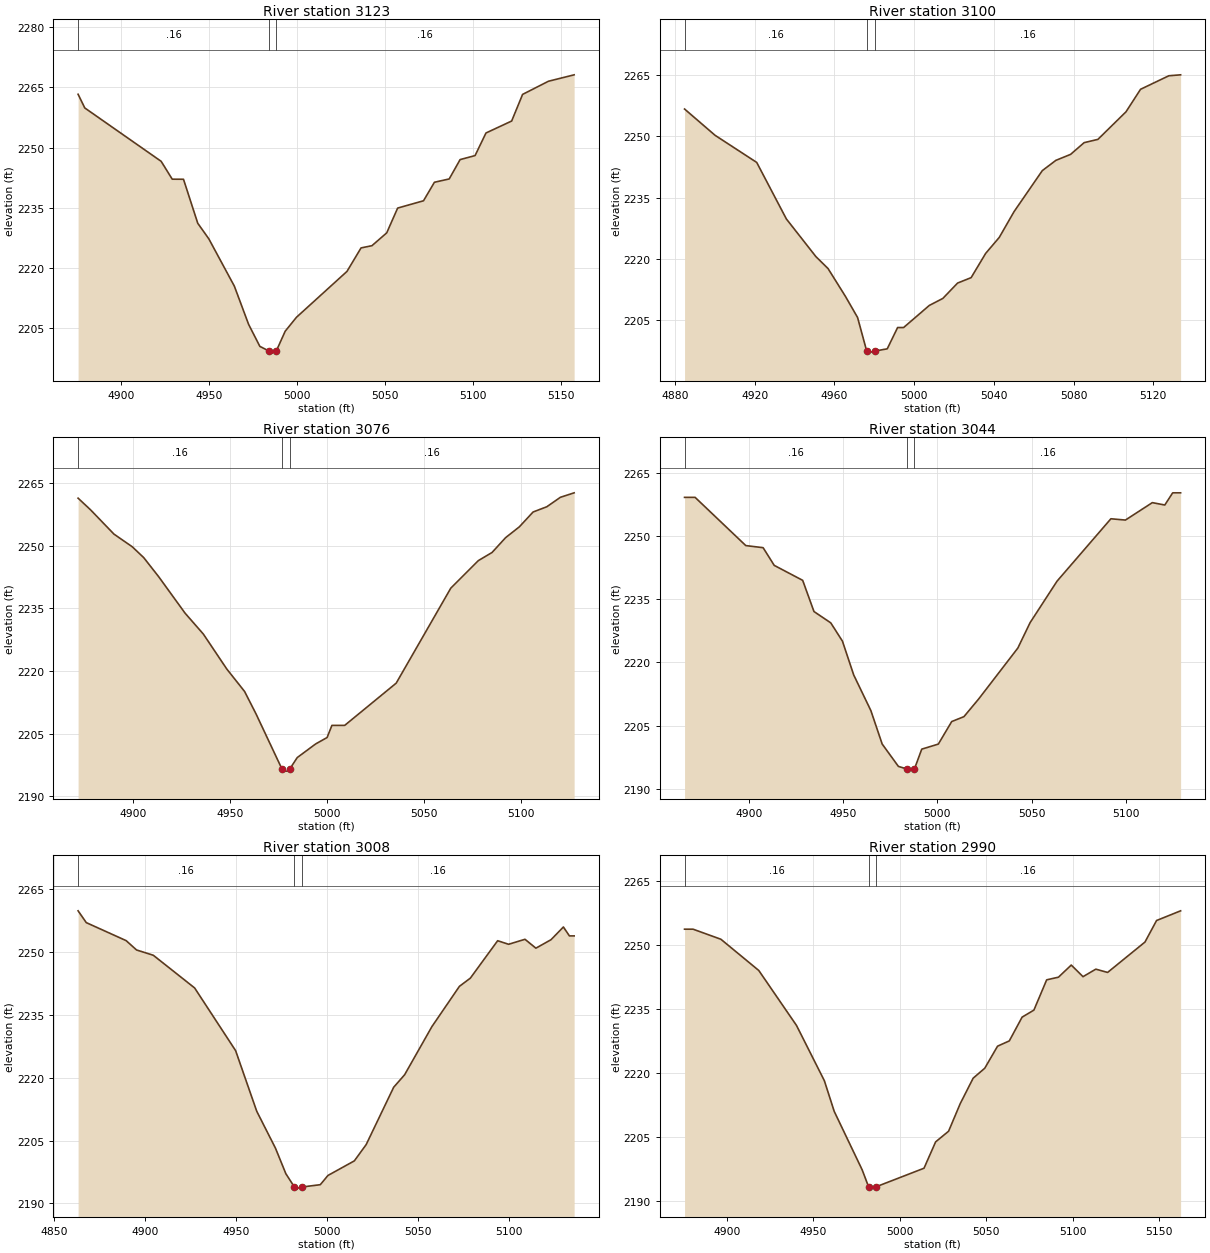
Type RM Length L Ch R = 1,3123,23,23,23
BEGIN DESCRIPTION:
elmc553
END DESCRIPTION:
XS GIS Cut Line= 3
      1511807.83      6772015.97      1511912.02      6771934.58
      1512000.63      6771813.93
#Sta/Elev= 30
  4875.7 2263.28  4879.5 2259.87  4922.9 2246.57  4929.2 2242.12  4935.6 2242.10
  4943.7 2231.14  4950.0 2227.25  4964.5 2215.47  4972.6 2205.95  4979.0 2200.46
  4984.3 2199.28  4984.6 2198.78  4988.3 2199.28  4993.4 2204.24  4999.8 2207.71
  5028.5 2219.14  5036.5 2224.99  5042.7 2225.55  5051.1 2228.75  5057.3 2234.92
  5072.0 2236.74  5078.2 2241.35  5086.6 2242.18  5092.8 2247.00  5101.3 2248.00
  5107.5 2253.63  5122.1 2256.61  5128.3 2263.24  5143.0 2266.52  5157.6 2268.12
#Mann=3,-1,0
  4875.7    0.16       0  4984.3    0.07       0  4988.3    0.16       0
Bank Sta=4984.3,4988.3
Exp/Cntr=0.3,0.1

Type RM Length L Ch R = 1,3100,24,24,24
BEGIN DESCRIPTION:
elmc552
END DESCRIPTION:
XS GIS Cut Line= 3
      1511828.45      6772022.48      1511918.53      6771959.53
      1512012.95      6771857.51
#Sta/Elev= 30
  4884.8 2256.70  4900.1 2250.27  4921.0 2243.63  4935.9 2229.78  4950.7 2220.58
  4956.8 2217.65  4965.5 2210.86  4971.6 2205.69  4976.2 2197.45  4976.4 2196.95
  4980.2 2197.45  4986.5 2198.00  4991.7 2203.21  4994.7 2203.21  5007.6 2208.62
  5014.4 2210.34  5021.8 2214.10  5028.6 2215.43  5035.9 2221.37  5042.7 2225.27
  5050.1 2231.56  5064.3 2241.62  5071.1 2244.13  5078.5 2245.60  5085.3 2248.47
  5092.2 2249.27  5106.3 2256.02  5113.6 2261.53  5127.8 2264.84  5133.7 2265.07
#Mann=3,-1,0
  4884.8    0.16       0  4976.2    0.07       0  4980.2    0.16       0
Bank Sta=4976.2,4980.2
Exp/Cntr=0.3,0.1

Type RM Length L Ch R = 1,3076,32,32,32
BEGIN DESCRIPTION:
elmc548
END DESCRIPTION:
XS GIS Cut Line= 3
      1511829.57      6772039.82      1511942.40      6771970.38
      1512030.42      6771883.44
#Sta/Elev= 30
  4871.4 2261.36  4877.8 2258.59  4889.9 2252.77  4899.4 2249.72  4905.3 2247.13
  4913.0 2242.58  4926.6 2233.87  4936.1 2228.83  4948.2 2220.47  4957.4 2215.09
  4963.3 2209.73  4976.7 2196.53  4976.9 2196.03  4980.4 2196.03  4980.7 2196.53
  4984.6 2199.28  4994.1 2202.54  5000.0 2204.07  5002.5 2206.98  5009.1 2206.98
  5035.7 2217.09  5063.9 2239.83  5078.1 2246.41  5085.2 2248.36  5092.2 2251.91
  5099.3 2254.50  5106.4 2258.05  5113.5 2259.31  5120.5 2261.57  5127.6 2262.64
#Mann=3,-1,0
  4871.4    0.16       0  4976.7    0.07       0  4980.7    0.16       0
Bank Sta=4976.7,4980.7
Exp/Cntr=0.3,0.1

Type RM Length L Ch R = 1,3044,36,36,36
BEGIN DESCRIPTION:
elmc549
END DESCRIPTION:
XS GIS Cut Line= 3
      1511850.15      6772069.13      1511960.84      6771996.43
      1512045.47      6771896.61
#Sta/Elev= 30
  4865.8 2259.28  4871.4 2259.28  4898.3 2247.81  4907.5 2247.31  4913.4 2243.10
  4928.5 2239.54  4934.5 2232.12  4943.4 2229.43  4949.6 2225.08  4955.6 2217.02
  4964.7 2208.55  4970.7 2200.60  4979.3 2195.29  4983.8 2194.66  4984.0 2194.16
  4987.8 2194.66  4991.7 2199.39  5000.5 2200.59  5007.6 2205.95  5014.1 2207.12
  5021.8 2211.26  5042.7 2223.43  5049.2 2229.47  5063.5 2239.34  5092.1 2254.19
  5099.8 2253.88  5114.1 2258.03  5120.7 2257.46  5124.9 2260.36  5129.1 2260.36
#Mann=3,-1,0
  4865.8    0.16       0  4983.8    0.07       0  4987.8    0.16       0
Bank Sta=4983.8,4987.8
Exp/Cntr=0.3,0.1

Type RM Length L Ch R = 1,3008,18,18,18
BEGIN DESCRIPTION:
elmc547
END DESCRIPTION:
XS GIS Cut Line= 3
      1511868.58      6772086.50      1511985.80      6772023.55
      1512062.85      6771907.44
#Sta/Elev= 30
  4863.4 2259.89  4867.9 2257.07  4889.8 2252.77  4895.5 2250.54  4904.7 2249.28
  4927.4 2241.47  4949.9 2226.50  4961.5 2212.02  4971.8 2203.19  4977.5 2197.09
  4982.2 2193.92  4982.4 2193.42  4986.2 2193.92  4996.4 2194.48  5000.6 2196.68
  5015.1 2200.17  5021.6 2204.06  5036.7 2217.75  5042.7 2220.73  5057.7 2232.24
  5072.8 2241.85  5078.8 2243.81  5093.8 2252.75  5099.8 2251.90  5108.8 2253.09
  5114.8 2250.97  5123.1 2252.99  5129.9 2256.03  5133.2 2253.90  5135.8 2253.90
#Mann=3,-1,0
  4863.4    0.16       0  4982.2    0.07       0  4986.2    0.16       0
Bank Sta=4982.2,4986.2
Exp/Cntr=0.3,0.1

Type RM Length L Ch R = 1,2990,22,22,22
BEGIN DESCRIPTION:
elmc550
END DESCRIPTION:
XS GIS Cut Line= 3
      1511891.40      6772093.00      1511998.82      6772034.40
      1512109.47      6771912.90
#Sta/Elev= 30
  4875.6 2253.74  4880.5 2253.74  4896.6 2251.38  4918.5 2244.06  4940.3 2231.18
  4956.4 2218.23  4962.1 2211.04  4978.3 2197.30  4982.0 2193.32  4982.2 2192.82
  4986.0 2193.32  5014.0 2197.72  5020.7 2203.89  5028.2 2206.39  5034.9 2212.83
  5042.4 2218.82  5049.1 2221.15  5056.5 2226.32  5063.3 2227.56  5070.7 2233.13
  5077.5 2234.77  5084.9 2241.87  5091.7 2242.49  5099.1 2245.33  5105.9 2242.61
  5113.3 2244.37  5120.1 2243.60  5141.7 2250.72  5148.4 2255.77  5162.3 2258.04
#Mann=3,-1,0
  4875.6    0.16       0  4982.0    0.07       0  4986.0    0.16       0
Bank Sta=4982,4986
Exp/Cntr=0.3,0.1

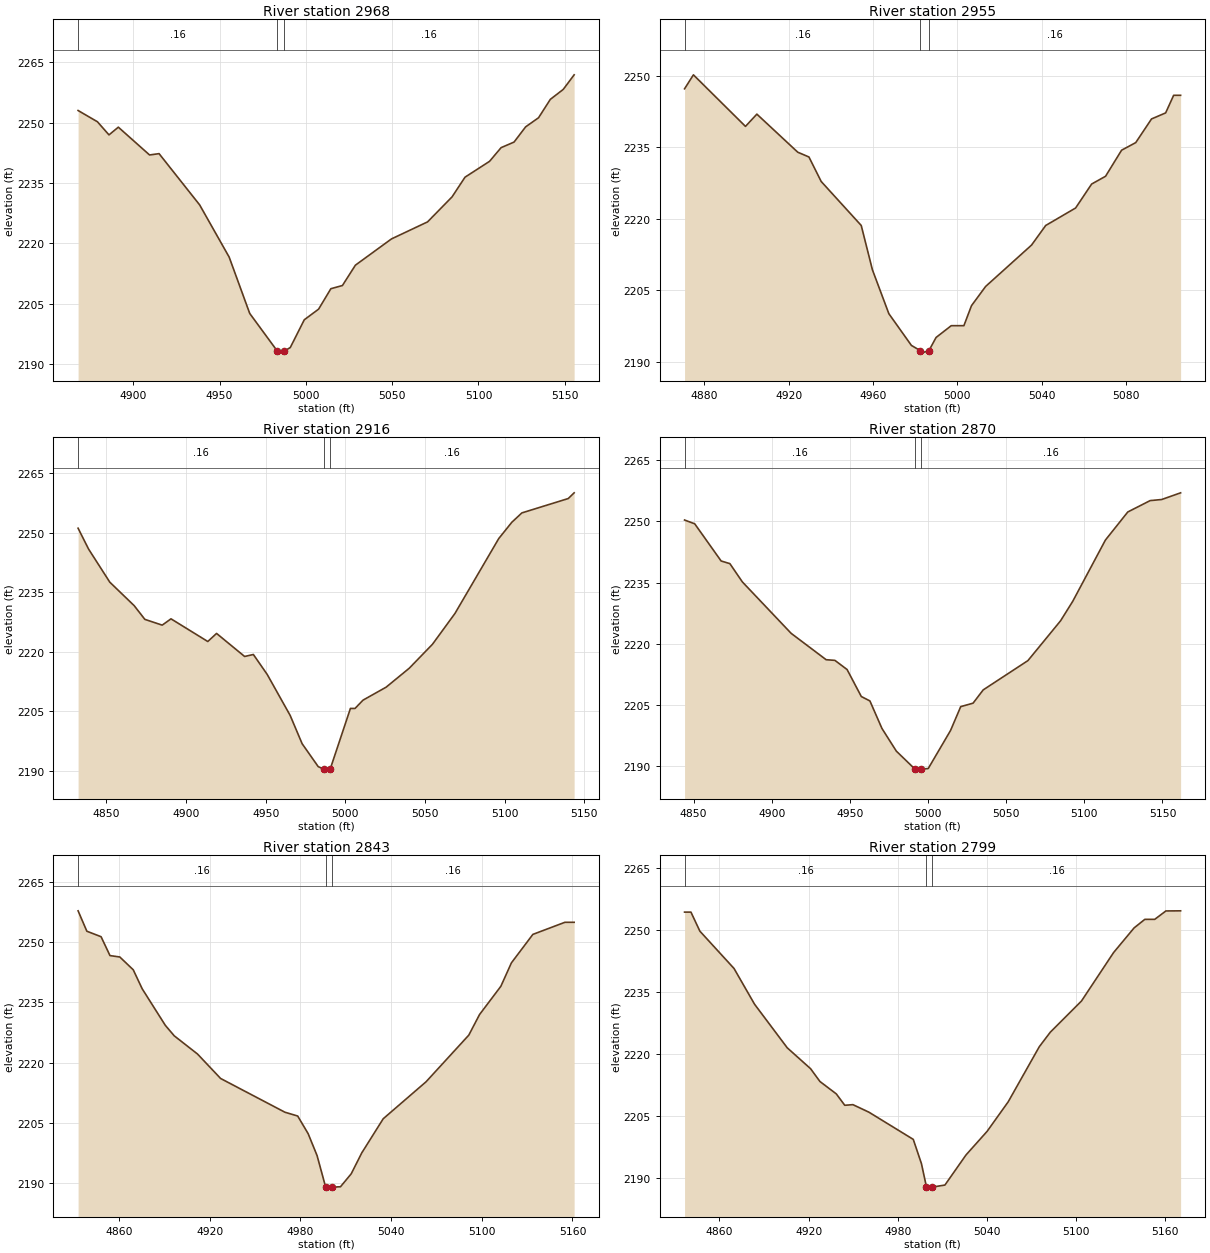
Type RM Length L Ch R = 1,2968,13,13,13
BEGIN DESCRIPTION:
elmc551
END DESCRIPTION:
XS GIS Cut Line= 3
      1511894.69      6772100.58      1512020.52      6772046.34
      1512120.70      6771934.32
#Sta/Elev= 30
  4868.1 2252.98  4879.3 2250.19  4886.0 2246.93  4891.4 2248.85  4909.5 2241.95
  4915.0 2242.28  4938.5 2229.57  4955.6 2216.62  4967.5 2202.65  4983.5 2193.30
  4983.8 2192.80  4987.5 2193.30  4991.0 2194.19  4999.1 2201.07  5007.4 2203.71
  5014.5 2208.78  5021.2 2209.57  5028.7 2214.61  5049.6 2221.13  5070.5 2225.35
  5084.7 2231.56  5092.2 2236.44  5106.4 2240.37  5113.1 2243.77  5120.6 2245.15
  5127.3 2248.92  5134.8 2251.19  5141.6 2255.74  5149.1 2258.22  5155.4 2261.83
#Mann=3,-1,0
  4868.1    0.16       0  4983.5    0.07       0  4987.5    0.16       0
Bank Sta=4983.5,4987.5
Exp/Cntr=0.3,0.1

Type RM Length L Ch R = 1,2955,39,39,39
BEGIN DESCRIPTION:
elmc398
END DESCRIPTION:
XS GIS Cut Line= 3
      1511904.44      6772103.84      1512025.39      6772057.84
      1512105.00      6771988.00
#Sta/Elev= 30
  4870.6 2247.26  4874.8 2250.19  4899.5 2239.38  4904.9 2241.95  4924.3 2233.97
  4929.6 2232.97  4935.4 2227.84  4954.4 2218.62  4959.7 2209.34  4967.5 2200.13
  4978.2 2193.48  4982.5 2192.36  4982.8 2191.86  4986.5 2192.36  4989.9 2195.14
  4997.1 2197.61  5003.1 2197.61  5006.7 2201.80  5013.4 2205.83  5035.2 2214.51
  5041.9 2218.61  5056.1 2222.28  5063.7 2227.30  5070.3 2228.93  5077.9 2234.39
  5084.6 2235.98  5092.1 2240.94  5098.8 2242.21  5102.6 2245.90  5105.9 2245.90
#Mann=3,-1,0
  4870.6    0.16       0  4982.5    0.07       0  4986.5    0.16       0
Bank Sta=4982.5,4986.5
Exp/Cntr=0.3,0.1

Type RM Length L Ch R = 1,2916,46,46,46
BEGIN DESCRIPTION:
elmc546
END DESCRIPTION:
XS GIS Cut Line= 3
      1511896.86      6772157.00      1512055.24      6772085.40
      1512164.46      6772001.89
#Sta/Elev= 30
  4832.3 2251.10  4838.9 2245.83  4852.2 2237.50  4867.5 2231.58  4874.2 2228.12
  4885.1 2226.67  4890.6 2228.26  4913.7 2222.54  4919.2 2224.58  4936.8 2218.77
  4942.3 2219.27  4951.0 2214.23  4965.4 2203.90  4972.9 2196.78  4983.0 2191.00
  4986.5 2190.37  4986.8 2189.87  4990.5 2190.37  5003.2 2205.67  5006.1 2205.67
  5011.1 2207.76  5025.6 2211.03  5040.1 2215.80  5054.7 2221.85  5068.8 2229.61
  5096.3 2248.50  5104.5 2252.60  5110.8 2254.96  5139.9 2258.58  5143.6 2260.02
#Mann=3,-1,0
  4832.3    0.16       0  4986.5    0.07       0  4990.5    0.16       0
Bank Sta=4986.5,4990.5
Exp/Cntr=0.3,0.1

Type RM Length L Ch R = 1,2870,27,27,27
BEGIN DESCRIPTION:
elmc545
END DESCRIPTION:
XS GIS Cut Line= 3
      1511921.81      6772204.75      1512048.73      6772141.83
      1512184.36      6772030.07
#Sta/Elev= 30
  4844.2 2250.33  4850.7 2249.40  4867.6 2240.28  4873.2 2239.63  4881.2 2235.14
  4912.4 2222.53  4934.8 2216.06  4940.4 2215.90  4948.2 2213.65  4957.3 2207.03
  4962.8 2205.95  4970.5 2199.20  4979.7 2193.64  4991.6 2189.23  4991.9 2188.73
  4995.4 2188.73  4995.6 2189.23  5000.1 2189.36  5014.4 2198.70  5020.9 2204.55
  5028.8 2205.40  5035.3 2208.66  5063.9 2215.84  5084.8 2225.61  5092.6 2230.40
  5113.5 2245.42  5127.8 2252.30  5142.1 2255.09  5149.5 2255.36  5161.6 2257.00
#Mann=3,-1,0
  4844.2    0.16       0  4991.6    0.07       0  4995.6    0.16       0
Bank Sta=4991.6,4995.6
Exp/Cntr=0.3,0.1

Type RM Length L Ch R = 1,2843,44,44,44
BEGIN DESCRIPTION:
elmc544
END DESCRIPTION:
XS GIS Cut Line= 3
      1511931.55      6772243.82      1512074.78      6772154.85
      1512188.70      6772043.09
#Sta/Elev= 30
  4832.9 2257.86  4838.7 2252.77  4848.1 2251.40  4854.0 2246.69  4860.5 2246.34
  4869.4 2243.14  4875.3 2238.41  4890.6 2229.29  4896.5 2226.67  4911.9 2222.13
  4927.2 2216.02  4969.7 2207.61  4978.2 2206.65  4985.1 2202.26  4991.0 2196.80
  4996.7 2188.91  4997.0 2188.41  5000.7 2188.91  5006.5 2189.00  5013.6 2192.23
  5020.6 2197.46  5034.8 2205.98  5063.1 2215.19  5091.4 2226.84  5098.5 2231.97
  5112.6 2239.02  5119.6 2244.88  5133.8 2251.98  5155.0 2255.00  5161.1 2255.00
#Mann=3,-1,0
  4832.9    0.16       0  4996.7    0.07       0  5000.7    0.16       0
Bank Sta=4996.7,5000.7
Exp/Cntr=0.3,0.1

Type RM Length L Ch R = 1,2799,39,39,39
BEGIN DESCRIPTION:
elmc543
END DESCRIPTION:
XS GIS Cut Line= 3
      1511952.15      6772257.94      1512104.07      6772188.48
      1512215.86      6772064.75
#Sta/Elev= 30
  4836.5 2254.34  4840.8 2254.34  4846.8 2249.73  4869.8 2240.68  4883.6 2232.03
  4905.6 2221.47  4921.3 2216.41  4927.6 2213.31  4938.6 2210.31  4944.3 2207.55
  4949.8 2207.70  4960.6 2205.87  4990.4 2199.29  4995.9 2193.42  4999.3 2187.74
  4999.6 2187.24  5003.3 2187.74  5011.7 2188.23  5025.9 2195.52  5040.1 2201.24
  5054.3 2208.40  5075.2 2221.73  5082.6 2225.25  5103.6 2232.81  5125.2 2244.54
  5139.0 2250.51  5146.2 2252.58  5152.9 2252.59  5160.4 2254.62  5170.3 2254.65
#Mann=3,-1,0
  4836.5    0.16       0  4999.3    0.07       0  5003.3    0.16       0
Bank Sta=4999.3,5003.3
Exp/Cntr=0.3,0.1

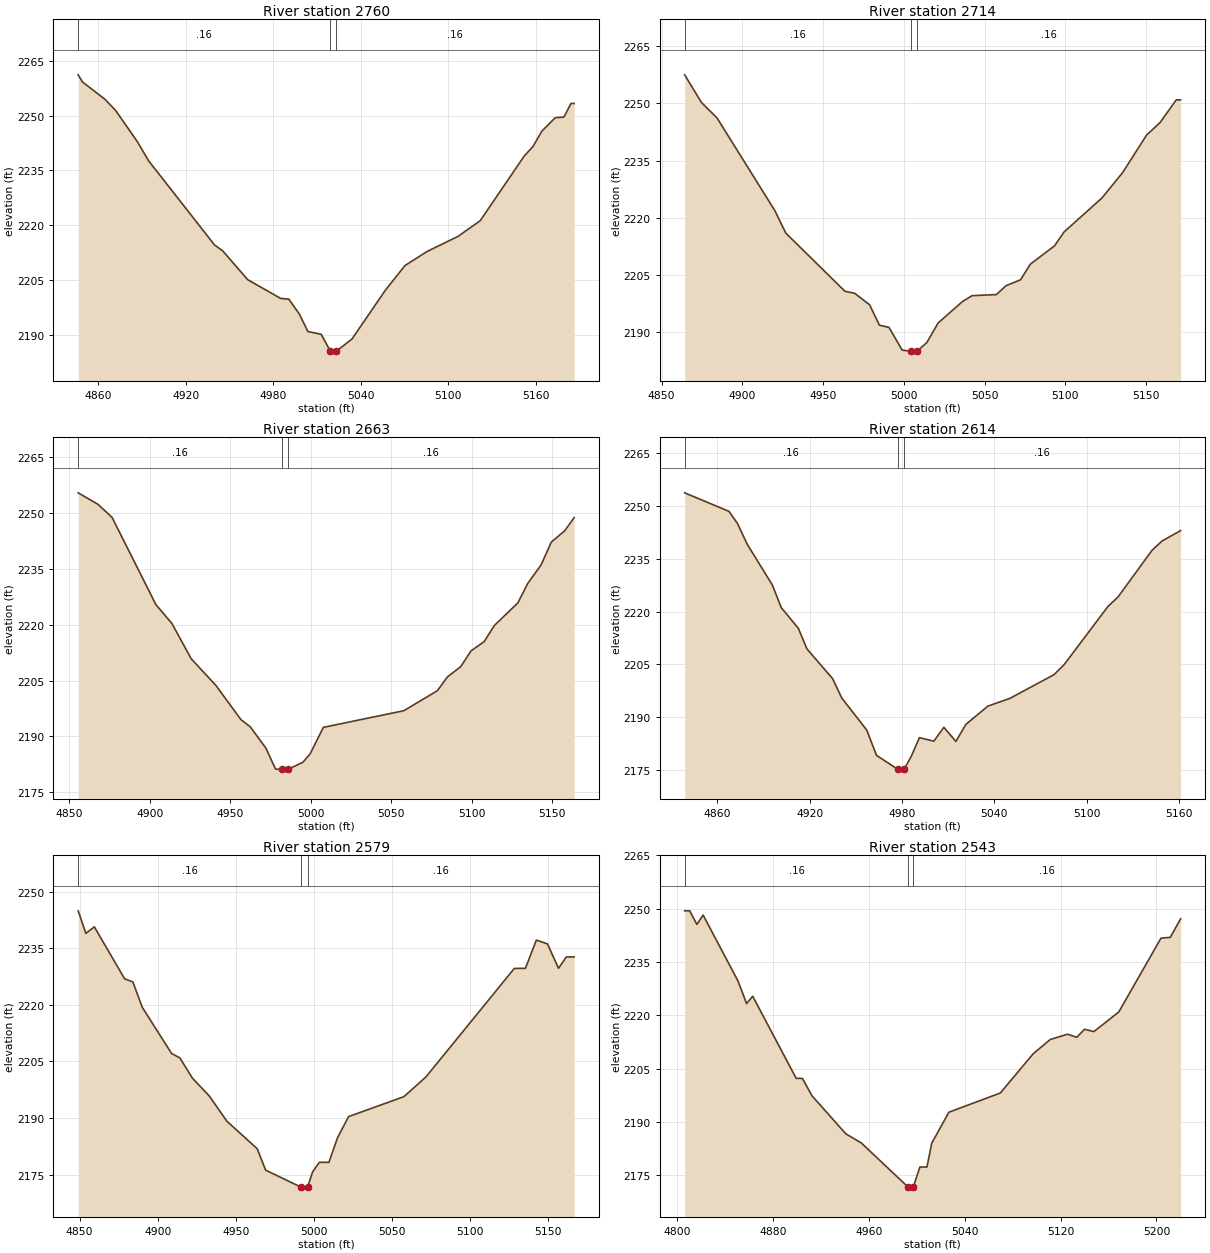
Type RM Length L Ch R = 1,2760,46,46,46
BEGIN DESCRIPTION:
elmc542
END DESCRIPTION:
XS GIS Cut Line= 3
      1511968.48      6772294.80      1512110.58      6772226.46
      1512263.60      6772127.70
#Sta/Elev= 30
  4846.4 2261.18  4849.3 2259.24  4864.7 2254.49  4872.0 2251.44  4886.9 2242.89
  4894.6 2237.65  4939.8 2214.58  4945.4 2212.97  4962.5 2205.08  4985.1 2199.94
  4990.7 2199.74  4997.9 2195.65  5003.8 2190.86  5012.9 2190.12  5019.2 2185.45
  5019.5 2184.95  5023.2 2185.45  5034.0 2188.83  5056.9 2202.21  5070.3 2208.94
  5085.5 2212.81  5106.6 2216.92  5121.8 2221.21  5152.1 2238.99  5158.0 2241.55
  5164.1 2245.76  5173.2 2249.42  5179.2 2249.60  5184.0 2253.33  5186.2 2253.33
#Mann=3,-1,0
  4846.4    0.16       0  5019.2    0.07       0  5023.2    0.16       0
Bank Sta=5019.2,5023.2
Exp/Cntr=0.3,0.1

Type RM Length L Ch R = 1,2714,51,51,51
BEGIN DESCRIPTION:
elmc541
END DESCRIPTION:
XS GIS Cut Line= 3
      1512017.28      6772336.04      1512134.45      6772264.44
      1512275.55      6772170.01
#Sta/Elev= 30
  4864.3 2257.52  4874.7 2250.25  4884.3 2246.22  4920.2 2221.82  4926.9 2215.97
  4963.6 2200.67  4969.5 2200.18  4978.8 2197.15  4984.9 2191.79  4990.8 2191.21
  4999.0 2185.24  5004.3 2184.95  5004.5 2184.45  5008.3 2184.95  5014.3 2187.27
  5021.3 2192.39  5036.3 2197.99  5042.3 2199.54  5057.3 2199.82  5063.3 2202.16
  5072.3 2203.71  5078.3 2207.79  5093.3 2212.60  5099.3 2216.29  5122.6 2225.15
  5135.4 2231.79  5150.4 2241.74  5158.7 2245.00  5168.7 2250.95  5171.4 2250.95
#Mann=3,-1,0
  4864.3    0.16       0  5004.3    0.07       0  5008.3    0.16       0
Bank Sta=5004.3,5008.3
Exp/Cntr=0.3,0.1

Type RM Length L Ch R = 1,2663,49,49,49
BEGIN DESCRIPTION:
elmc540
END DESCRIPTION:
XS GIS Cut Line= 3
      1512044.41      6772375.11      1512164.84      6772304.59
      1512299.15      6772202.77
#Sta/Elev= 30
  4855.5 2255.39  4867.8 2252.30  4876.5 2248.82  4903.8 2225.35  4913.7 2220.33
  4925.7 2210.84  4941.0 2203.71  4956.6 2194.51  4962.4 2192.57  4972.1 2186.85
  4978.1 2181.22  4981.9 2181.18  4982.2 2180.68  4985.9 2181.18  4995.1 2183.06
  4999.6 2185.34  5007.8 2192.43  5057.8 2196.90  5078.6 2202.26  5084.9 2205.98
  5093.2 2208.75  5099.5 2212.95  5107.7 2215.44  5114.0 2219.77  5128.6 2225.83
  5134.8 2231.08  5143.1 2236.06  5149.4 2242.16  5157.7 2245.19  5163.6 2248.73
#Mann=3,-1,0
  4855.5    0.16       0  4981.9    0.07       0  4985.9    0.16       0
Bank Sta=4981.9,4985.9
Exp/Cntr=0.3,0.1

Type RM Length L Ch R = 1,2614,35,35,35
BEGIN DESCRIPTION:
elmc538
END DESCRIPTION:
XS GIS Cut Line= 3
      1512058.46      6772407.69      1512199.56      6772339.31
      1512326.51      6772232.97
#Sta/Elev= 30
  4838.7 2253.80  4867.5 2248.53  4873.1 2245.03  4879.3 2239.22  4895.6 2227.66
  4901.5 2221.15  4912.6 2215.26  4918.2 2209.40  4934.9 2200.93  4940.8 2195.45
  4957.1 2186.30  4963.4 2179.13  4977.3 2175.14  4977.6 2174.64  4981.3 2175.14
  4986.0 2178.84  4991.3 2184.16  5000.7 2183.16  5007.2 2187.11  5015.0 2183.08
  5021.5 2187.93  5035.8 2193.13  5050.1 2195.33  5078.8 2202.08  5085.3 2204.89
  5113.9 2221.50  5120.4 2224.17  5142.5 2237.44  5149.0 2240.09  5161.1 2243.06
#Mann=3,-1,0
  4838.7    0.16       0  4977.3    0.07       0  4981.3    0.16       0
Bank Sta=4977.3,4981.3
Exp/Cntr=0.3,0.1

Type RM Length L Ch R = 1,2579,36,36,36
BEGIN DESCRIPTION:
elmc539
END DESCRIPTION:
XS GIS Cut Line= 3
      1512086.73      6772415.26      1512232.11      6772359.92
      1512347.16      6772245.96
#Sta/Elev= 30
  4849.1 2244.95  4854.0 2238.95  4859.4 2240.71  4878.8 2226.94  4884.1 2226.08
  4890.1 2219.37  4908.9 2207.10  4914.2 2205.94  4922.2 2200.58  4932.9 2195.91
  4944.3 2189.15  4963.7 2181.85  4969.1 2176.17  4991.9 2171.64  4992.1 2171.14
  4995.9 2171.64  4999.2 2175.75  5003.5 2178.25  5009.6 2178.25  5015.1 2184.76
  5022.2 2190.38  5057.6 2195.66  5071.7 2200.89  5128.3 2229.68  5135.4 2229.70
  5142.4 2237.18  5149.5 2236.19  5156.6 2229.71  5161.6 2232.73  5166.6 2232.73
#Mann=3,-1,0
  4849.1    0.16       0  4991.9    0.07       0  4995.9    0.16       0
Bank Sta=4991.9,4995.9
Exp/Cntr=0.3,0.1

Type RM Length L Ch R = 1,2543,49,49,49
BEGIN DESCRIPTION:
elmc536
END DESCRIPTION:
XS GIS Cut Line= 3
      1512061.76      6772435.88      1512254.90      6772388.14
      1512420.45      6772250.72
#Sta/Elev= 30
  4806.1 2249.36  4810.3 2249.36  4816.3 2245.54  4821.5 2248.17  4850.6 2229.65
  4857.8 2223.28  4862.9 2225.36  4899.2 2202.29  4904.4 2202.26  4912.4 2197.39
  4940.6 2186.71  4953.6 2184.12  4992.9 2171.65  4993.1 2171.15  4996.9 2171.65
  5002.5 2177.37  5008.4 2177.37  5012.4 2184.06  5026.7 2192.76  5069.7 2198.17
  5097.0 2209.16  5111.3 2213.19  5125.7 2214.69  5133.5 2213.83  5140.0 2216.07
  5147.8 2215.42  5168.6 2220.95  5203.8 2241.67  5211.6 2241.91  5220.2 2247.12
#Mann=3,-1,0
  4806.1    0.16       0  4992.9    0.07       0  4996.9    0.16       0
Bank Sta=4992.9,4996.9
Exp/Cntr=0.3,0.1