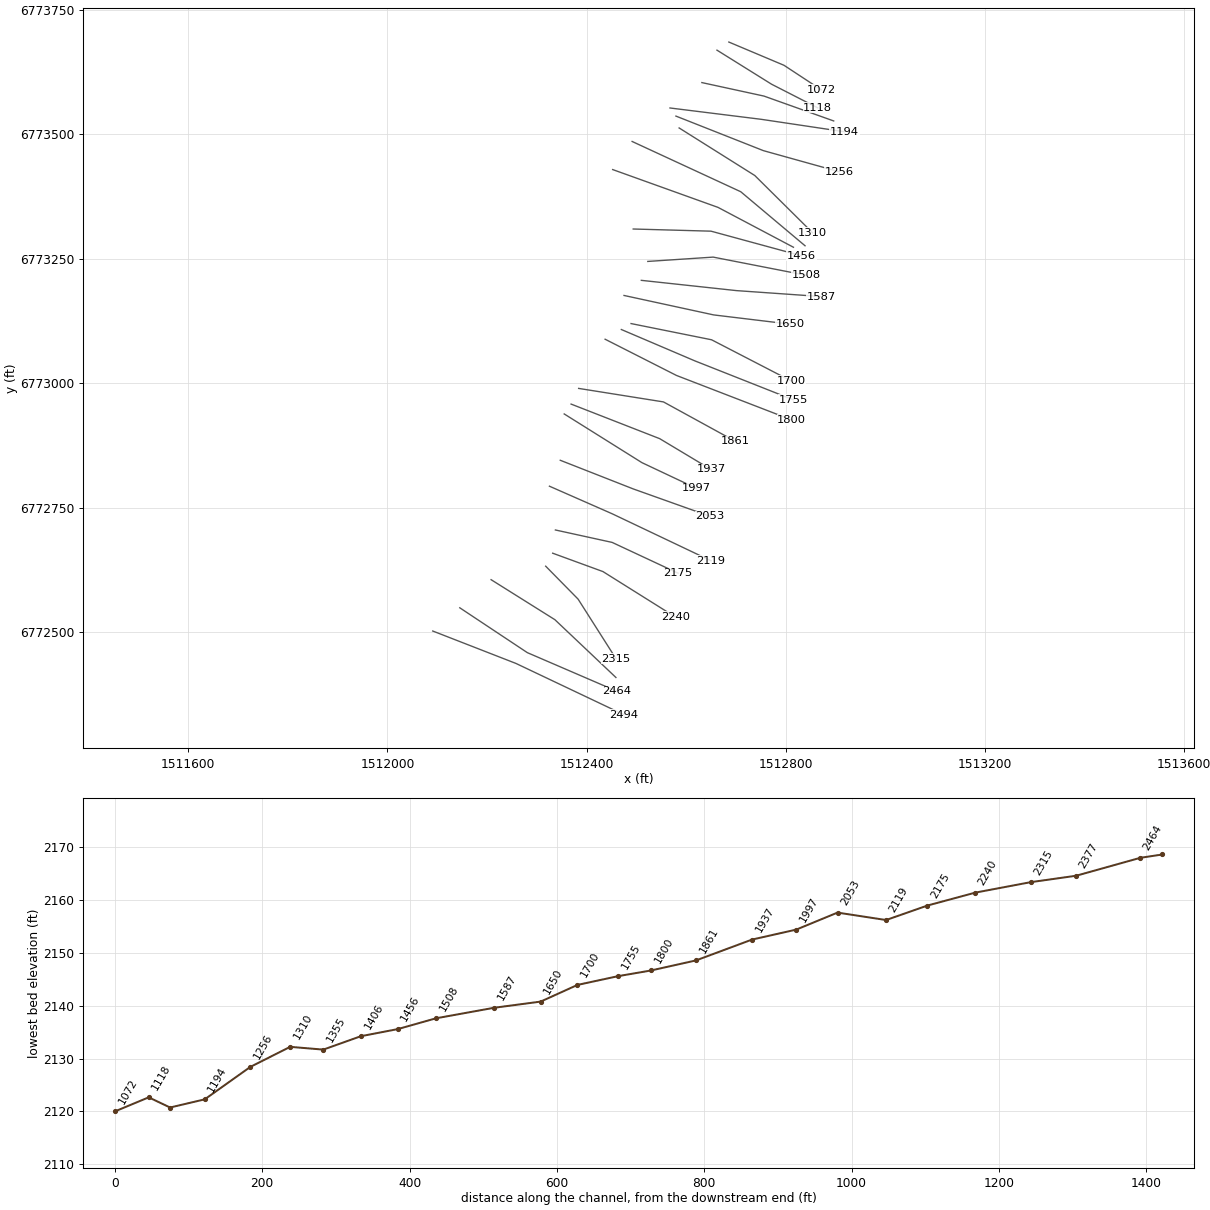
HEC-RAS study Elm 46.prj: Elm 46 Base Level Engineering

--- Elm 46.g01 (geometry) --- (continued)

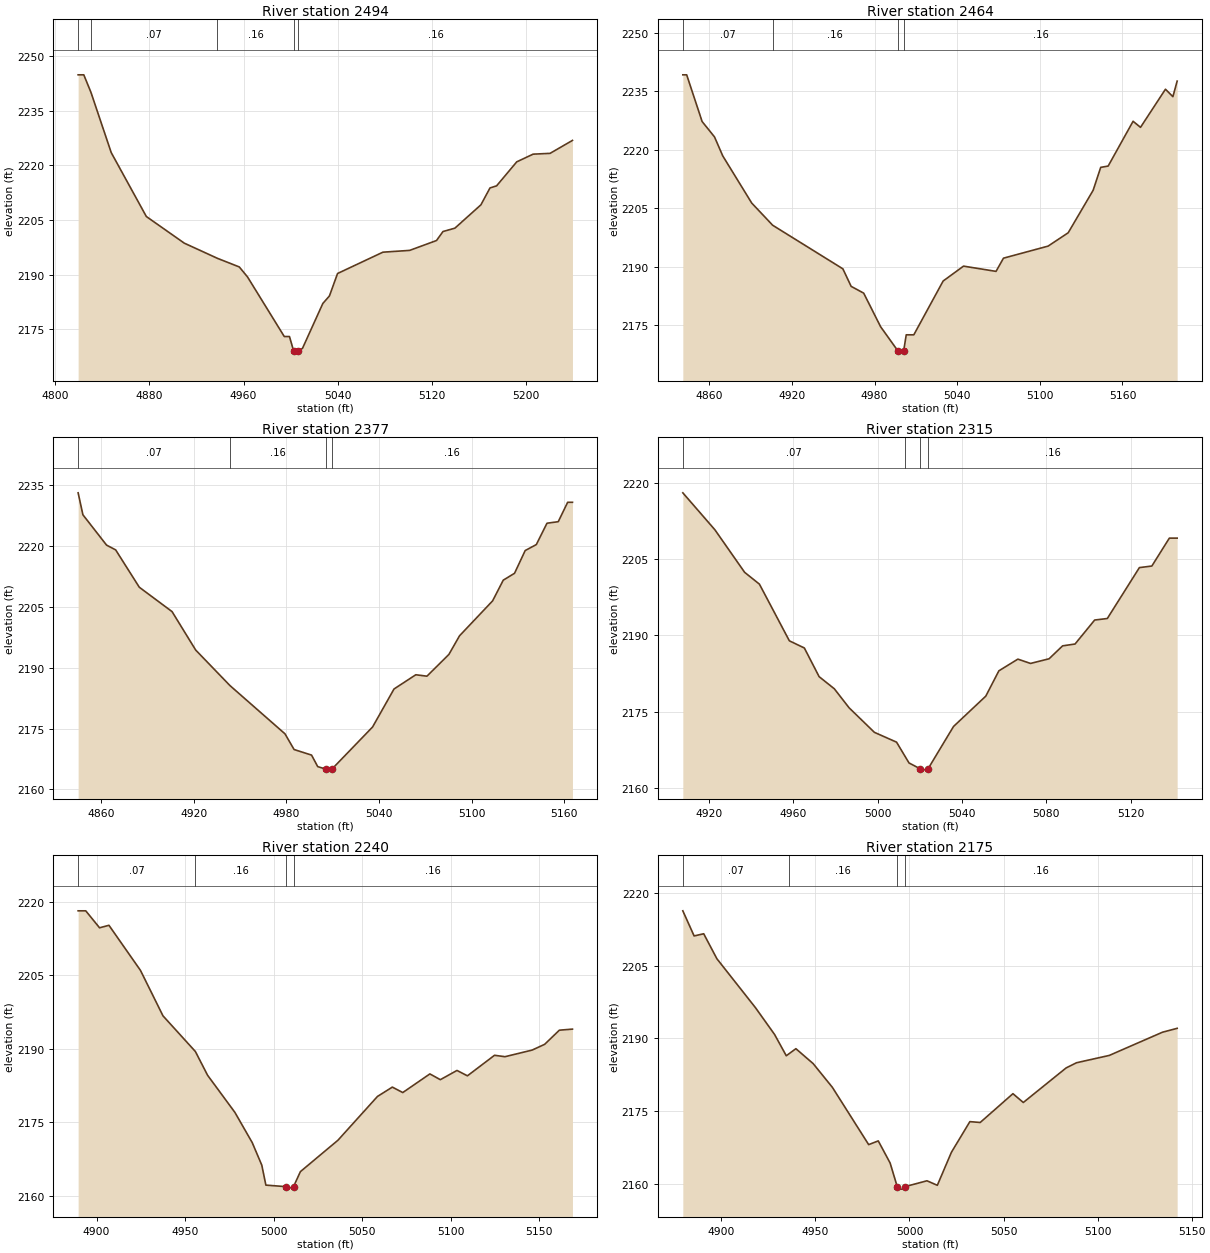
Type RM Length L Ch R = 1,2494,30,30,30
BEGIN DESCRIPTION:
elmc537
END DESCRIPTION:
XS GIS Cut Line= 3
      1512091.02      6772502.08      1512258.15      6772436.96
      1512475.15      6772333.89
#Sta/Elev= 30
  4819.6 2244.88  4824.4 2244.88  4830.4 2240.15  4847.7 2223.53  4877.5 2206.00
  4909.7 2198.69  4937.8 2194.53  4956.4 2192.16  4963.4 2189.41  4994.6 2173.06
  4999.0 2173.06  5002.6 2169.01  5002.9 2168.51  5006.6 2169.01  5010.1 2169.86
  5027.3 2182.13  5032.9 2184.19  5039.8 2190.36  5078.3 2196.21  5101.0 2196.70
  5123.8 2199.41  5129.3 2201.88  5139.4 2202.80  5161.5 2209.21  5169.2 2213.84
  5174.8 2214.41  5191.9 2221.00  5205.8 2223.11  5220.2 2223.33  5239.2 2226.88
#Mann=5,-1,0
  4819.6    0.16       0  4830.4    0.07       0  4937.8    0.16       0
  5002.6    0.07       0  5006.6    0.16       0
Bank Sta=5002.6,5006.6
Exp/Cntr=0.3,0.1

Type RM Length L Ch R = 1,2464,87,87,87
BEGIN DESCRIPTION:
elmc535
END DESCRIPTION:
XS GIS Cut Line= 3
      1512145.33      6772548.71      1512280.94      6772458.67
      1512461.03      6772381.02
#Sta/Elev= 30
  4840.8 2239.16  4843.6 2239.16  4854.8 2227.20  4863.8 2223.26  4869.8 2218.39
  4890.8 2206.33  4906.0 2200.64  4957.0 2189.47  4963.0 2184.98  4972.1 2183.25
  4984.4 2174.64  4997.1 2168.38  4997.3 2167.88  5001.1 2168.38  5003.0 2172.57
  5008.5 2172.57  5029.8 2186.35  5044.6 2190.16  5068.2 2188.82  5073.6 2192.20
  5106.0 2195.29  5120.6 2198.71  5138.7 2209.59  5144.2 2215.46  5149.6 2215.79
  5167.7 2227.26  5173.1 2225.71  5191.2 2235.47  5196.6 2233.57  5199.7 2237.55
#Mann=4,-1,0
  4840.8    0.07       0  4906.0    0.16       0  4997.1    0.07       0
  5001.1    0.16       0
Bank Sta=4997.1,5001.1
Exp/Cntr=0.3,0.1

Type RM Length L Ch R = 1,2377,62,62,62
BEGIN DESCRIPTION:
elmc534
END DESCRIPTION:
XS GIS Cut Line= 3
      1512208.23      6772605.16      1512336.28      6772524.85
      1512458.89      6772408.76
#Sta/Elev= 30
  4845.2 2233.06  4848.3 2227.65  4863.6 2220.18  4869.5 2219.00  4884.8 2209.80
  4906.0 2203.80  4921.3 2194.33  4943.5 2185.57  4979.1 2173.69  4985.0 2169.82
  4996.3 2168.45  5000.3 2165.61  5005.5 2165.00  5005.8 2164.50  5009.5 2165.00
  5035.8 2175.37  5049.7 2184.74  5063.8 2188.24  5071.0 2187.89  5085.2 2193.24
  5092.1 2197.84  5113.5 2206.44  5120.4 2211.54  5127.7 2213.24  5134.6 2218.84
  5141.8 2220.31  5148.7 2225.57  5156.0 2225.95  5162.1 2230.73  5165.2 2230.73
#Mann=4,-1,0
  4845.2    0.07       0  4943.5    0.16       0  5005.5    0.07       0
  5009.5    0.16       0
Bank Sta=5005.5,5009.5
Exp/Cntr=0.3,0.1

Type RM Length L Ch R = 1,2315,75,75,75
BEGIN DESCRIPTION:
elmc533
END DESCRIPTION:
XS GIS Cut Line= 3
      1512317.83      6772632.28      1512382.94      6772566.09
      1512458.88      6772446.75
#Sta/Elev= 30
  4907.7 2218.02  4922.9 2210.75  4937.0 2202.38  4944.0 2200.06  4958.2 2188.91
  4965.3 2187.50  4972.3 2181.86  4979.5 2179.48  4986.5 2175.74  4998.5 2170.91
  5009.0 2168.98  5013.0 2166.21  5014.9 2164.89  5020.0 2163.78  5020.2 2163.28
  5024.0 2163.78  5036.0 2172.06  5051.3 2178.03  5057.5 2183.01  5066.5 2185.31
  5072.5 2184.46  5081.3 2185.38  5087.7 2187.92  5093.6 2188.28  5102.9 2193.00
  5108.9 2193.30  5124.1 2203.31  5130.0 2203.62  5138.3 2209.11  5142.0 2209.11
#Mann=4,-1,0
  4907.7    0.07       0  5013.0    0.16       0  5020.0    0.07       0
  5024.0    0.16       0
Bank Sta=5020,5024
Exp/Cntr=0.3,0.1

Type RM Length L Ch R = 1,2240,65,65,65
BEGIN DESCRIPTION:
elmc532
END DESCRIPTION:
XS GIS Cut Line= 3
      1512331.91      6772658.33      1512432.85      6772621.43
      1512578.26      6772530.27
#Sta/Elev= 30
  4889.6 2218.22  4893.9 2218.22  4901.7 2214.75  4907.0 2215.26  4924.8 2206.04
  4937.5 2196.75  4955.8 2189.45  4962.7 2184.59  4978.1 2177.01  4987.9 2170.82
  4993.3 2166.21  4995.6 2162.13  5007.2 2161.81  5007.5 2161.31  5011.2 2161.81
  5015.1 2164.89  5036.3 2171.31  5058.6 2180.26  5067.0 2182.17  5072.9 2181.06
  5088.2 2184.87  5094.1 2183.69  5103.5 2185.58  5109.4 2184.48  5124.7 2188.68
  5130.6 2188.39  5145.9 2189.74  5153.0 2190.92  5161.3 2193.81  5168.7 2194.03
#Mann=4,-1,0
  4889.6    0.07       0  4955.8    0.16       0  5007.2    0.07       0
  5011.2    0.16       0
Bank Sta=5007.2,5011.2
Exp/Cntr=0.3,0.1

Type RM Length L Ch R = 1,2175,56,56,56
BEGIN DESCRIPTION:
elmc531
END DESCRIPTION:
XS GIS Cut Line= 3
      1512337.34      6772704.98      1512451.29      6772680.02
      1512583.70      6772618.16
#Sta/Elev= 30
  4879.5 2216.28  4885.5 2211.10  4890.6 2211.55  4897.6 2206.40  4918.1 2196.31
  4928.3 2190.76  4934.5 2186.38  4936.0 2186.81  4939.6 2187.84  4948.8 2184.76
  4959.0 2179.87  4978.3 2168.05  4983.4 2168.82  4989.7 2164.26  4993.5 2159.37
  4993.7 2158.87  4997.2 2158.87  4997.5 2159.37  5009.3 2160.59  5014.8 2159.66
  5022.3 2166.48  5032.1 2172.79  5037.6 2172.62  5055.0 2178.56  5060.5 2176.74
  5083.3 2183.88  5088.8 2184.94  5106.2 2186.45  5134.5 2191.24  5142.3 2192.04
#Mann=4,-1,0
  4879.5    0.07       0  4936.0    0.16       0  4993.5    0.07       0
  4997.5    0.16       0
Bank Sta=4993.5,4997.5
Exp/Cntr=0.3,0.1

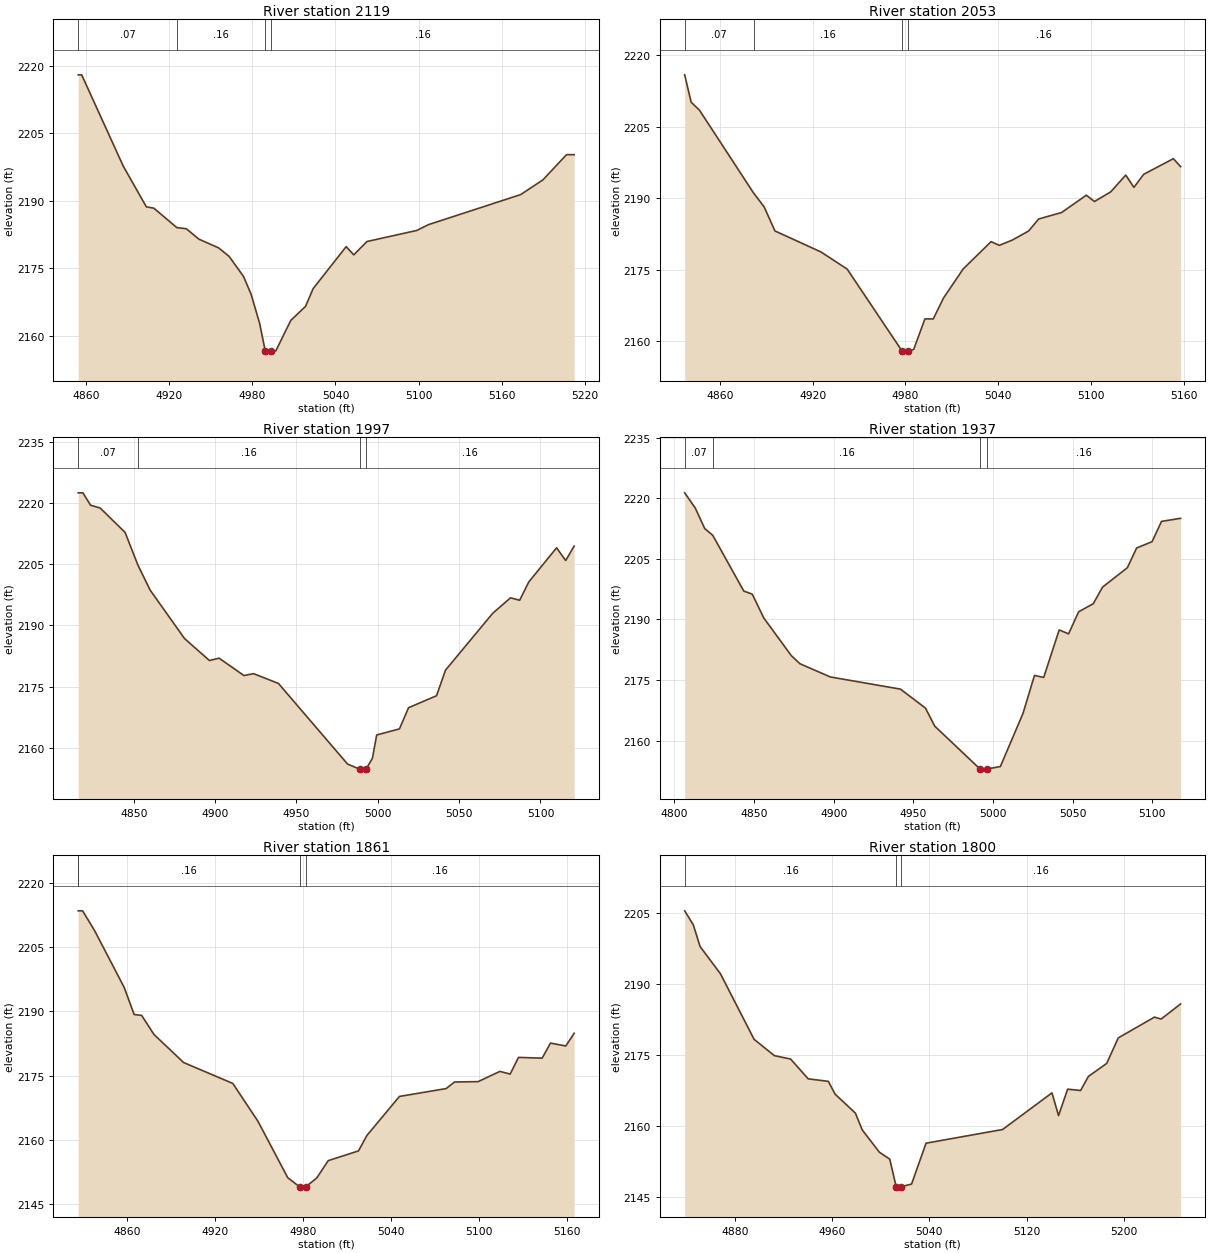
Type RM Length L Ch R = 1,2119,66,66,66
BEGIN DESCRIPTION:
elmc530
END DESCRIPTION:
XS GIS Cut Line= 3
      1512325.38      6772792.89      1512451.29      6772737.53
      1512649.86      6772643.13
#Sta/Elev= 30
  4854.6 2217.98  4857.1 2217.98  4887.0 2197.73  4903.7 2188.65  4909.1 2188.35
  4925.7 2184.03  4932.5 2183.78  4941.6 2181.46  4955.8 2179.53  4963.4 2177.62
  4973.7 2173.19  4979.2 2169.23  4985.3 2162.78  4989.4 2156.64  4989.7 2156.14
  4993.2 2156.14  4993.4 2156.64  4997.0 2156.64  5007.8 2163.41  5018.4 2166.52
  5023.9 2170.47  5047.7 2179.80  5053.2 2177.98  5062.7 2180.94  5098.6 2183.40
  5107.0 2184.69  5173.4 2191.36  5189.5 2194.64  5206.5 2200.24  5212.0 2200.24
#Mann=4,-1,0
  4854.6    0.07       0  4925.7    0.16       0  4989.4    0.07       0
  4993.4    0.16       0
Bank Sta=4989.4,4993.4
Exp/Cntr=0.3,0.1

Type RM Length L Ch R = 1,2053,56,56,56
BEGIN DESCRIPTION:
elmc529
END DESCRIPTION:
XS GIS Cut Line= 3
      1512347.12      6772844.95      1512493.61      6772787.44
      1512647.54      6772732.54
#Sta/Elev= 30
  4837.2 2215.85  4841.4 2210.11  4846.8 2208.43  4881.8 2191.07  4888.6 2188.19
  4895.6 2183.14  4925.4 2178.73  4942.3 2175.15  4977.7 2158.04  4977.9 2157.54
  4981.7 2158.04  4985.3 2158.28  4992.6 2164.71  4998.0 2164.71  5004.6 2169.07
  5017.3 2175.16  5035.4 2180.90  5040.7 2180.12  5049.1 2181.22  5059.7 2183.13
  5066.2 2185.65  5081.0 2187.00  5097.0 2190.63  5102.3 2189.31  5112.8 2191.33
  5122.5 2194.84  5127.8 2192.27  5134.1 2195.00  5153.3 2198.28  5158.0 2196.62
#Mann=4,-1,0
  4837.2    0.07       0  4881.8    0.16       0  4977.7    0.07       0
  4981.7    0.16       0
Bank Sta=4977.7,4981.7
Exp/Cntr=0.3,0.1

Type RM Length L Ch R = 1,1997,60,60,60
BEGIN DESCRIPTION:
elmc397
END DESCRIPTION:
XS GIS Cut Line= 3
      1512355.02      6772937.99      1512511.11      6772840.18
      1512620.27      6772788.67
#Sta/Elev= 30
  4815.8 2222.47  4818.7 2222.47  4823.4 2219.44  4829.3 2218.75  4844.6 2212.79
  4852.5 2204.79  4860.0 2198.67  4881.2 2186.78  4896.5 2181.41  4902.4 2181.99
  4917.7 2177.73  4923.6 2178.20  4938.9 2175.80  4981.4 2156.06  4988.8 2154.83
  4989.0 2154.33  4992.8 2154.83  4996.7 2157.51  4999.3 2163.18  5013.3 2164.67
  5018.9 2169.86  5036.1 2172.79  5041.6 2179.05  5070.6 2192.96  5081.6 2196.77
  5087.2 2196.17  5092.8 2200.64  5109.9 2209.01  5115.5 2205.89  5120.7 2209.44
#Mann=4,-1,0
  4815.8    0.07       0  4852.5    0.16       0  4988.8    0.07       0
  4992.8    0.16       0
Bank Sta=4988.8,4992.8
Exp/Cntr=0.3,0.1

Type RM Length L Ch R = 1,1937,76,76,76
BEGIN DESCRIPTION:
elmc527
END DESCRIPTION:
XS GIS Cut Line= 3
      1512368.84      6772957.79      1512546.78      6772888.35
      1512649.84      6772826.52
#Sta/Elev= 30
  4806.5 2221.34  4813.1 2217.61  4819.1 2212.49  4824.1 2210.83  4843.6 2197.02
  4848.9 2196.26  4856.1 2190.39  4873.4 2181.04  4878.8 2179.04  4897.9 2175.76
  4941.9 2172.75  4957.6 2168.05  4963.4 2163.59  4991.9 2152.95  4992.1 2152.45
  4995.9 2152.95  5004.6 2153.59  5018.8 2166.74  5026.0 2176.14  5031.8 2175.65
  5041.5 2187.40  5047.4 2186.43  5053.7 2191.89  5062.9 2193.90  5068.7 2197.99
  5084.3 2202.81  5090.1 2207.68  5099.8 2209.25  5105.7 2214.27  5117.7 2215.03
#Mann=4,-1,0
  4806.5    0.07       0  4824.1    0.16       0  4991.9    0.07       0
  4995.9    0.16       0
Bank Sta=4991.9,4995.9
Exp/Cntr=0.3,0.1

Type RM Length L Ch R = 1,1861,61,61,61
BEGIN DESCRIPTION:
elmc528
END DESCRIPTION:
XS GIS Cut Line= 3
      1512384.05      6772989.26      1512554.38      6772962.14
      1512699.35      6772882.67
#Sta/Elev= 30
  4826.9 2213.46  4827.0 2213.46  4829.9 2213.46  4838.0 2208.88  4858.2 2195.60
  4865.0 2189.27  4870.1 2189.06  4878.5 2184.61  4898.7 2178.06  4932.2 2173.18
  4949.4 2164.31  4969.6 2151.20  4977.8 2149.02  4978.0 2148.52  4981.8 2149.02
  4989.4 2151.13  4997.2 2155.17  5017.8 2157.44  5023.5 2161.02  5045.7 2170.15
  5077.5 2171.98  5083.2 2173.52  5099.3 2173.60  5114.1 2175.99  5121.1 2175.37
  5126.8 2179.26  5142.9 2179.08  5148.6 2182.60  5159.0 2181.92  5164.7 2184.89
#Mann=4,-1,0
  4826.9    0.07       0  4827.0    0.16       0  4977.8    0.07       0
  4981.8    0.16       0
Bank Sta=4977.8,4981.8
Exp/Cntr=0.3,0.1

Type RM Length L Ch R = 1,1800,45,45,45
BEGIN DESCRIPTION:
elmc525
END DESCRIPTION:
XS GIS Cut Line= 3
      1512437.19      6773088.01      1512580.42      6773015.31
      1512811.85      6772925.96
#Sta/Elev= 30
  4838.3 2205.39  4845.4 2202.43  4851.0 2197.85  4867.7 2192.13  4895.5 2178.26
  4912.2 2174.81  4925.6 2174.09  4940.1 2169.91  4956.7 2169.38  4962.3 2166.67
  4979.0 2162.67  4984.6 2159.14  4998.7 2154.43  5007.3 2152.95  5012.6 2147.12
  5012.8 2146.62  5016.6 2147.12  5025.3 2147.70  5037.2 2156.32  5100.3 2159.21
  5141.0 2166.95  5146.4 2162.14  5153.9 2167.73  5164.6 2167.45  5171.0 2170.42
  5186.1 2173.17  5195.6 2178.55  5225.5 2182.95  5230.9 2182.53  5247.0 2185.73
#Mann=3,-1,0
  4838.3    0.16       0  5012.6    0.07       0  5016.6    0.16       0
Bank Sta=5012.6,5016.6
Exp/Cntr=0.3,0.1

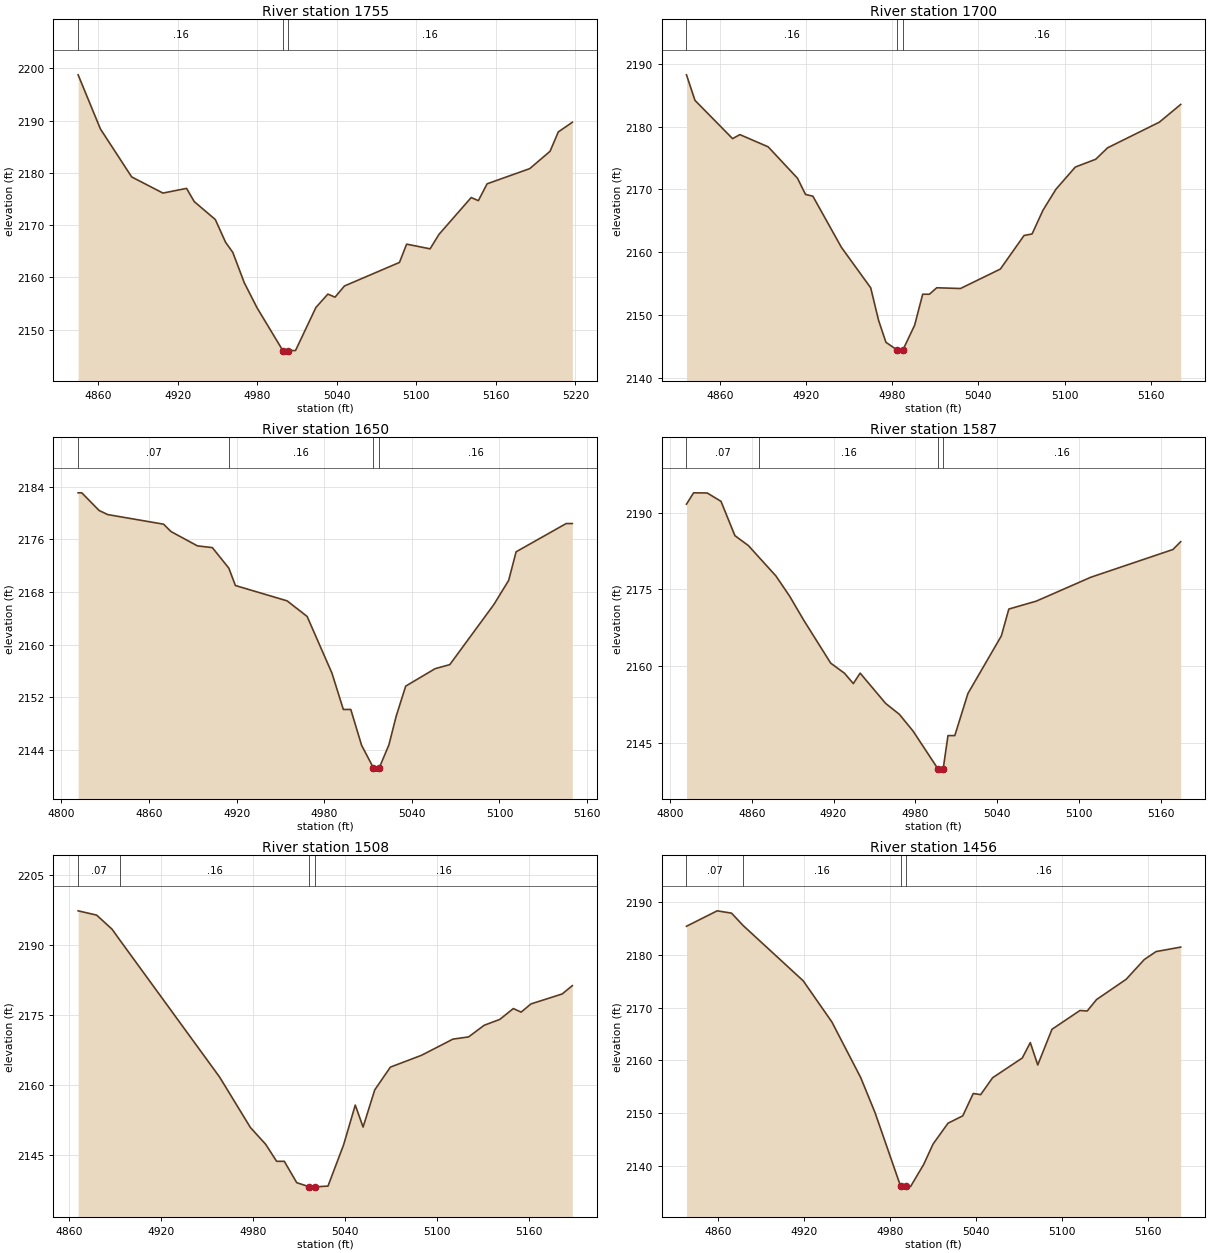
Type RM Length L Ch R = 1,1755,55,55,55
BEGIN DESCRIPTION:
elmc526
END DESCRIPTION:
XS GIS Cut Line= 3
      1512469.76      6773107.53      1512617.31      6773044.60
      1512814.81      6772966.47
#Sta/Elev= 30
  4844.9 2198.75  4861.7 2188.41  4885.3 2179.23  4908.9 2176.14  4926.7 2177.04
  4932.5 2174.51  4948.4 2171.08  4956.1 2166.75  4961.6 2164.79  4970.2 2159.02
  4979.8 2154.24  4999.3 2146.04  4999.6 2145.54  5003.3 2146.04  5008.9 2146.04
  5024.3 2154.28  5033.3 2156.83  5038.7 2156.24  5045.8 2158.38  5087.3 2162.88
  5092.7 2166.38  5110.4 2165.48  5117.1 2168.24  5141.4 2175.29  5146.8 2174.69
  5153.4 2177.91  5185.6 2180.82  5200.9 2184.13  5207.1 2187.83  5217.7 2189.68
#Mann=3,-1,0
  4844.9    0.16       0  4999.3    0.07       0  5003.3    0.16       0
Bank Sta=4999.3,5003.3
Exp/Cntr=0.3,0.1

Type RM Length L Ch R = 1,1700,50,50,50
BEGIN DESCRIPTION:
elmc524
END DESCRIPTION:
XS GIS Cut Line= 3
      1512489.25      6773119.48      1512650.95      6773086.92
      1512810.19      6773004.59
#Sta/Elev= 30
  4836.7 2188.25  4842.6 2184.18  4868.8 2178.08  4873.9 2178.72  4893.6 2176.77
  4914.0 2171.77  4919.6 2169.18  4924.7 2168.91  4944.6 2160.75  4965.0 2154.30
  4970.5 2149.10  4975.6 2145.62  4983.4 2144.39  4983.6 2143.89  4987.4 2144.39
  4995.6 2148.34  5001.2 2153.28  5005.9 2153.28  5011.0 2154.31  5027.5 2154.19
  5055.3 2157.29  5071.8 2162.64  5077.4 2162.89  5085.0 2166.68  5094.0 2170.01
  5107.5 2173.55  5121.7 2174.79  5130.0 2176.62  5166.0 2180.70  5180.9 2183.53
#Mann=3,-1,0
  4836.7    0.16       0  4983.4    0.07       0  4987.4    0.16       0
Bank Sta=4983.4,4987.4
Exp/Cntr=0.3,0.1

Type RM Length L Ch R = 1,1650,63,63,63
BEGIN DESCRIPTION:
elmc523
END DESCRIPTION:
XS GIS Cut Line= 3
      1512475.17      6773175.90      1512655.29      6773136.83
      1512808.27      6773118.39
#Sta/Elev= 30
  4811.5 2183.07  4814.0 2183.07  4825.9 2180.38  4831.8 2179.76  4870.0 2178.30
  4875.1 2177.18  4893.2 2175.00  4903.4 2174.74  4914.7 2171.61  4919.2 2168.97
  4954.6 2166.64  4968.3 2164.27  4985.3 2155.65  4993.1 2150.12  4998.2 2150.12
  5005.6 2144.67  5013.7 2141.24  5013.9 2140.74  5017.4 2140.74  5017.7 2141.24
  5024.3 2144.73  5029.3 2149.11  5035.8 2153.67  5056.0 2156.33  5066.0 2156.94
  5096.2 2166.09  5106.3 2169.75  5111.4 2174.10  5145.7 2178.40  5149.9 2178.40
#Mann=4,-1,0
  4811.5    0.07       0  4914.7    0.16       0  5013.7    0.07       0
  5017.7    0.16       0
Bank Sta=5013.7,5017.7
Exp/Cntr=0.3,0.1

Type RM Length L Ch R = 1,1587,79,79,79
BEGIN DESCRIPTION:
elmc521
END DESCRIPTION:
XS GIS Cut Line= 3
      1512509.87      6773206.28      1512700.86      6773185.66
      1512870.64      6773173.77
#Sta/Elev= 30
  4812.2 2191.63  4817.4 2193.84  4827.4 2193.81  4837.5 2192.18  4847.7 2185.49
  4857.6 2183.55  4865.7 2181.17  4877.7 2177.65  4887.8 2173.70  4897.8 2169.16
  4917.9 2160.64  4928.0 2158.67  4934.5 2156.65  4939.5 2158.69  4958.2 2152.78
  4968.2 2150.67  4978.3 2147.39  4996.4 2140.08  4996.7 2139.58  5000.2 2139.58
  5000.4 2140.08  5003.9 2146.51  5008.9 2146.51  5018.5 2154.71  5043.0 2165.94
  5048.5 2171.18  5068.6 2172.72  5108.7 2177.39  5168.8 2182.79  5174.5 2184.32
#Mann=4,-1,0
  4812.2    0.07       0  4865.7    0.16       0  4996.4    0.07       0
  5000.4    0.16       0
Bank Sta=4996.4,5000.4
Exp/Cntr=0.3,0.1

Type RM Length L Ch R = 1,1508,52,52,52
BEGIN DESCRIPTION:
elmc522
END DESCRIPTION:
XS GIS Cut Line= 3
      1512522.89      6773244.26      1512654.20      6773252.94
      1512841.47      6773216.34
#Sta/Elev= 30
  4866.1 2197.22  4878.2 2196.30  4888.3 2193.26  4893.7 2190.78  4958.4 2161.60
  4978.5 2150.79  4988.5 2147.18  4995.6 2143.55  5000.6 2143.55  5008.7 2138.98
  5016.9 2138.09  5017.1 2137.59  5020.6 2137.59  5020.9 2138.09  5029.1 2138.24
  5039.3 2147.09  5046.9 2155.60  5052.0 2150.89  5059.6 2158.85  5069.8 2163.73
  5090.2 2166.28  5110.6 2169.73  5120.8 2170.20  5131.0 2172.70  5141.2 2173.96
  5150.0 2176.28  5155.1 2175.52  5161.5 2177.27  5181.9 2179.41  5188.5 2181.19
#Mann=4,-1,0
  4866.1    0.07       0  4893.7    0.16       0  5016.9    0.07       0
  5020.9    0.16       0
Bank Sta=5016.9,5020.9
Exp/Cntr=0.3,0.1

Type RM Length L Ch R = 1,1456,50,50,50
BEGIN DESCRIPTION:
elmc518
END DESCRIPTION:
XS GIS Cut Line= 3
      1512493.59      6773309.36      1512649.86      6773305.02
      1512831.62      6773255.55
#Sta/Elev= 30
  4838.1 2185.47  4859.5 2188.40  4869.5 2187.96  4877.6 2185.61  4919.5 2175.11
  4939.5 2167.30  4959.6 2156.74  4969.6 2150.08  4987.5 2136.05  4987.7 2135.55
  4991.5 2136.05  4994.4 2136.05  5003.5 2140.22  5010.1 2144.12  5020.5 2148.07
  5030.8 2149.47  5038.1 2153.71  5043.3 2153.50  5051.6 2156.70  5072.3 2160.45
  5077.9 2163.38  5083.1 2159.13  5093.0 2165.90  5112.5 2169.47  5117.6 2169.38
  5124.1 2171.55  5144.8 2175.41  5157.4 2179.15  5165.6 2180.66  5182.8 2181.51
#Mann=4,-1,0
  4838.1    0.07       0  4877.6    0.16       0  4987.5    0.07       0
  4991.5    0.16       0
Bank Sta=4987.5,4991.5
Exp/Cntr=0.3,0.1

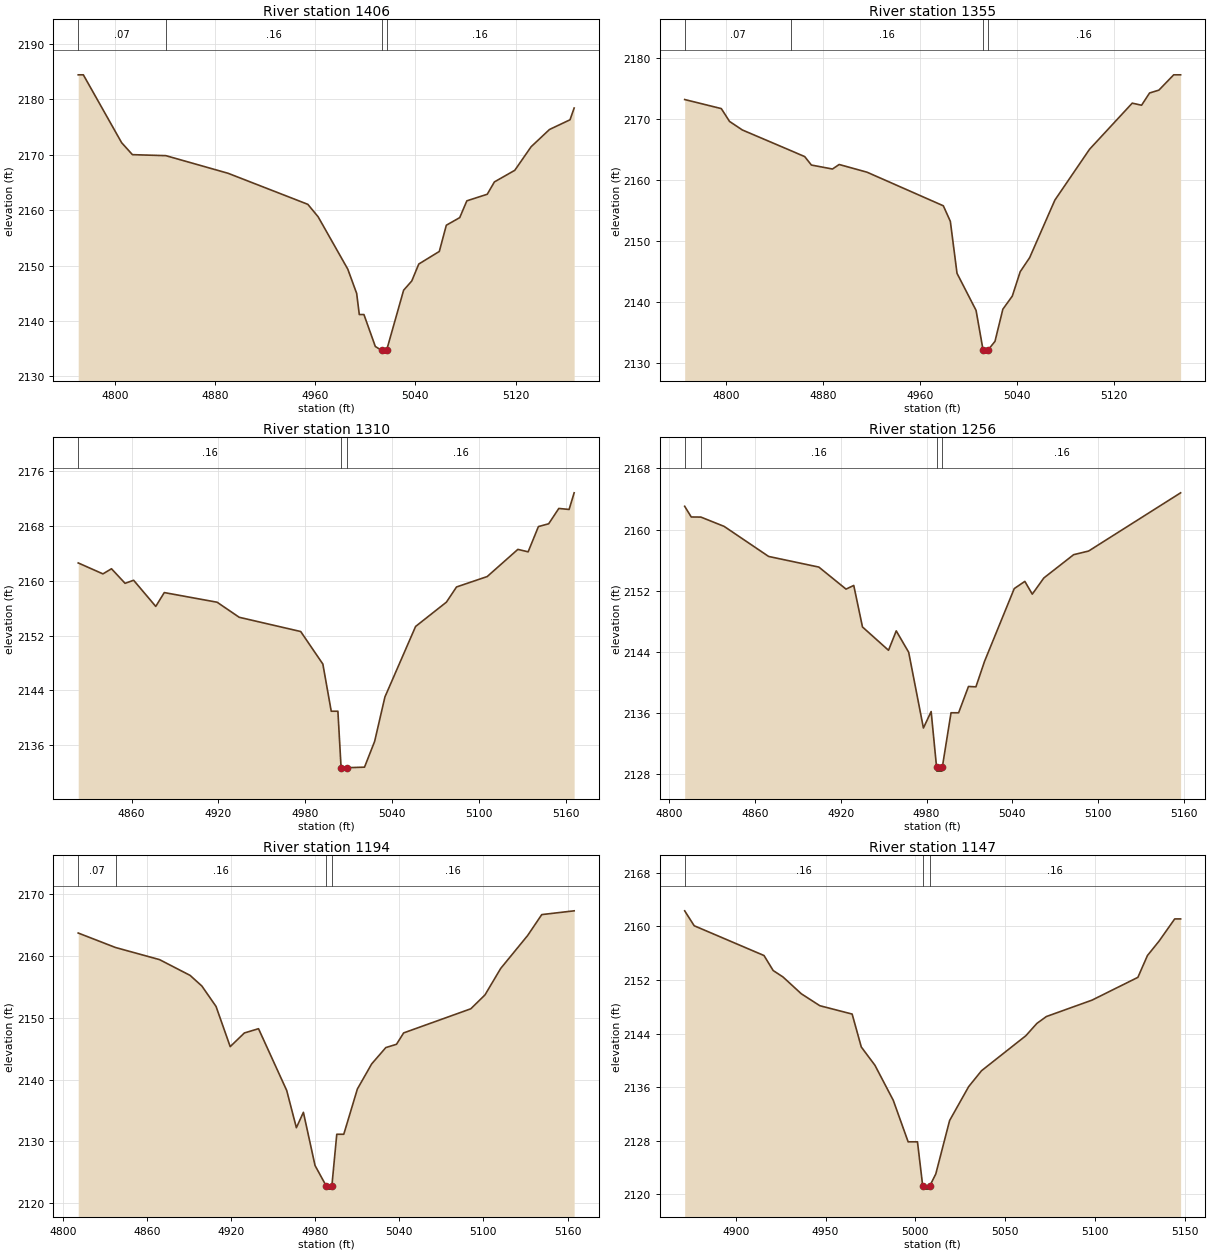
Type RM Length L Ch R = 1,1406,51,51,51
BEGIN DESCRIPTION:
elmc520
END DESCRIPTION:
XS GIS Cut Line= 3
      1512452.36      6773428.73      1512663.97      6773352.76
      1512815.38      6773272.73
#Sta/Elev= 30
  4770.7 2184.41  4774.8 2184.41  4805.4 2172.16  4814.0 2170.01  4840.7 2169.83
  4890.4 2166.65  4954.1 2161.05  4962.3 2158.81  4986.0 2149.36  4993.1 2144.98
  4995.2 2141.17  4998.9 2141.17  5008.0 2135.41  5013.0 2134.71  5013.3 2134.21
  5017.0 2134.71  5030.6 2145.56  5037.1 2147.22  5042.7 2150.28  5059.1 2152.55
  5064.7 2157.28  5075.4 2158.65  5081.1 2161.68  5097.4 2162.87  5103.1 2165.09
  5119.4 2167.19  5132.4 2171.43  5147.1 2174.55  5163.5 2176.30  5166.8 2178.42
#Mann=4,-1,0
  4770.7    0.07       0  4840.7    0.16       0  5013.0    0.07       0
  5017.0    0.16       0
Bank Sta=5013,5017
Exp/Cntr=0.3,0.1

Type RM Length L Ch R = 1,1355,45,45,45
BEGIN DESCRIPTION:
elmc519
END DESCRIPTION:
XS GIS Cut Line= 3
      1512491.42      6773485.15      1512709.54      6773384.23
      1512838.67      6773275.72
#Sta/Elev= 30
  4765.7 2173.14  4795.9 2171.66  4802.7 2169.56  4813.3 2168.16  4853.1 2164.80
  4864.7 2163.81  4870.2 2162.43  4887.6 2161.78  4893.1 2162.52  4916.1 2161.26
  4979.0 2155.77  4984.8 2153.22  4990.3 2144.73  5006.0 2138.67  5011.8 2132.18
  5012.1 2131.68  5015.8 2132.18  5021.6 2133.60  5028.1 2138.86  5035.9 2141.01
  5042.4 2144.99  5050.2 2147.29  5071.0 2156.70  5099.6 2165.01  5134.8 2172.55
  5142.5 2172.21  5149.1 2174.21  5156.8 2174.68  5169.0 2177.18  5174.7 2177.18
#Mann=4,-1,0
  4765.7    0.07       0  4853.1    0.16       0  5011.8    0.07       0
  5015.8    0.16       0
Bank Sta=5011.8,5015.8
Exp/Cntr=0.3,0.1

Type RM Length L Ch R = 1,1310,54,54,54
BEGIN DESCRIPTION:
elmc517
END DESCRIPTION:
XS GIS Cut Line= 3
      1512585.80      6773512.29      1512737.75      6773416.78
      1512853.78      6773301.83
#Sta/Elev= 30
  4823.1 2162.61  4840.2 2161.01  4846.1 2161.76  4855.5 2159.63  4861.4 2160.08
  4876.7 2156.26  4882.6 2158.28  4919.1 2156.87  4934.4 2154.67  4976.9 2152.59
  4992.2 2147.84  4998.0 2140.95  5002.6 2140.95  5004.8 2132.70  5005.1 2132.20
  5008.8 2132.70  5021.0 2132.78  5028.0 2136.55  5035.1 2143.03  5056.3 2153.33
  5077.6 2156.88  5084.6 2159.10  5105.8 2160.62  5127.0 2164.59  5134.1 2164.23
  5141.2 2167.92  5148.3 2168.33  5155.3 2170.57  5162.4 2170.42  5165.9 2172.85
#Mann=3,-1,0
  4823.1    0.16       0  5004.8    0.07       0  5008.8    0.16       0
Bank Sta=5004.8,5008.8
Exp/Cntr=0.3,0.1

Type RM Length L Ch R = 1,1256,62,62,62
BEGIN DESCRIPTION:
elmc516
END DESCRIPTION:
XS GIS Cut Line= 3
      1512579.37      6773536.12      1512755.11      6773466.70
      1512907.07      6773424.37
#Sta/Elev= 30
  4810.9 2163.05  4815.5 2161.65  4822.2 2161.64  4838.5 2160.42  4869.6 2156.49
  4904.7 2155.10  4923.7 2152.22  4929.1 2152.70  4935.2 2147.27  4953.4 2144.22
  4958.8 2146.76  4967.5 2143.96  4977.8 2134.06  4983.2 2136.21  4987.0 2128.92
  4987.2 2128.42  4990.7 2128.42  4991.0 2128.92  4997.1 2136.05  5002.4 2136.05
  5009.3 2139.49  5014.5 2139.44  5020.5 2142.76  5041.3 2152.29  5048.7 2153.23
  5053.9 2151.56  5062.0 2153.68  5082.8 2156.72  5093.3 2157.20  5157.6 2164.81
#Mann=4,-1,0
  4810.9    0.07       0  4822.2    0.16       0  4987.0    0.07       0
  4991.0    0.16       0
Bank Sta=4987,4991
Exp/Cntr=0.3,0.1

Type RM Length L Ch R = 1,1194,47,47,47
BEGIN DESCRIPTION:
elmc515
END DESCRIPTION:
XS GIS Cut Line= 3
      1512567.43      6773552.41      1512750.77      6773529.63
      1512917.86      6773504.67
#Sta/Elev= 30
  4811.0 2163.70  4837.6 2161.36  4869.0 2159.40  4890.8 2156.85  4899.2 2155.13
  4909.3 2151.83  4919.4 2145.33  4929.5 2147.54  4939.6 2148.23  4959.7 2138.24
  4966.6 2132.22  4971.6 2134.71  4979.9 2126.11  4987.9 2122.79  4988.2 2122.29
  4991.7 2122.29  4991.9 2122.79  4995.4 2131.16  5000.4 2131.16  5010.1 2138.48
  5020.3 2142.54  5030.4 2145.18  5038.0 2145.71  5043.1 2147.55  5091.0 2151.45
  5101.1 2153.69  5112.3 2157.97  5131.5 2163.29  5141.6 2166.68  5164.7 2167.29
#Mann=4,-1,0
  4811.0    0.07       0  4837.6    0.16       0  4987.9    0.07       0
  4991.9    0.16       0
Bank Sta=4987.9,4991.9
Exp/Cntr=0.3,0.1

Type RM Length L Ch R = 1,1147,29,29,29
BEGIN DESCRIPTION:
elmc514
END DESCRIPTION:
XS GIS Cut Line= 3
      1512631.46      6773603.40      1512756.20      6773576.29
      1512896.21      6773526.36
#Sta/Elev= 30
  4871.5 2162.34  4876.8 2160.11  4915.7 2155.66  4920.8 2153.42  4926.3 2152.45
  4936.5 2149.94  4946.8 2148.16  4964.8 2146.91  4969.9 2141.99  4977.5 2139.26
  4987.7 2134.03  4996.0 2127.82  5001.2 2127.82  5004.1 2121.25  5004.3 2120.75
  5007.8 2120.75  5008.1 2121.25  5011.4 2123.02  5019.1 2131.00  5029.7 2136.06
  5036.9 2138.45  5061.6 2143.68  5067.7 2145.51  5073.0 2146.54  5098.5 2149.00
  5124.0 2152.40  5129.3 2155.65  5135.9 2157.85  5144.5 2161.13  5147.8 2161.13
#Mann=3,-1,0
  4871.5    0.16       0  5004.1    0.07       0  5008.1    0.16       0
Bank Sta=5004.1,5008.1
Exp/Cntr=0.3,0.1

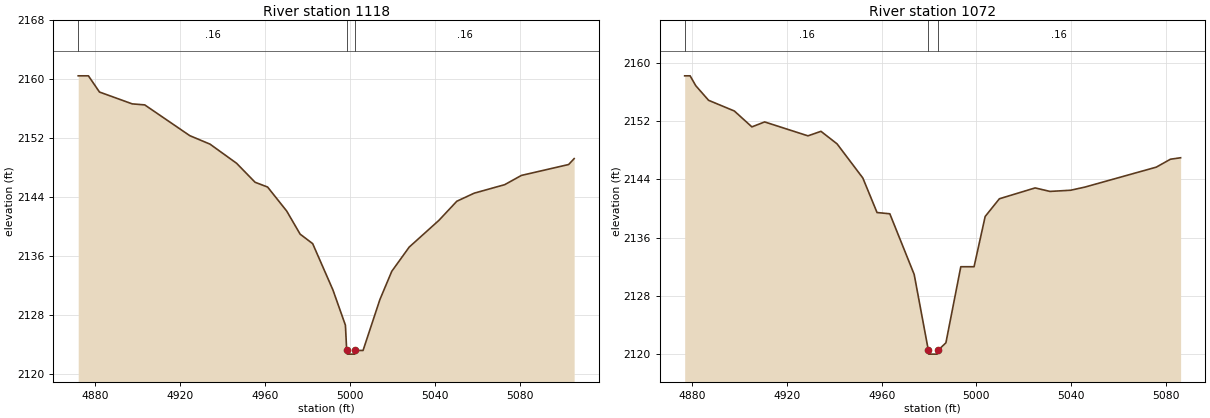
Type RM Length L Ch R = 1,1118,46,46,46
BEGIN DESCRIPTION:
elmc513
END DESCRIPTION:
XS GIS Cut Line= 3
      1512661.80      6773668.52      1512771.39      6773600.16
      1512864.10      6773552.73
#Sta/Elev= 30
  4872.0 2160.48  4876.8 2160.48  4882.0 2158.28  4897.4 2156.67  4903.3 2156.53
  4924.5 2152.35  4934.0 2151.20  4946.5 2148.60  4955.2 2146.02  4961.1 2145.37
  4970.1 2142.10  4976.4 2138.97  4982.3 2137.68  4991.8 2131.41  4997.7 2126.60
  4998.3 2123.17  4998.6 2122.67  5002.1 2122.67  5002.3 2123.17  5006.0 2123.17
  5013.9 2130.07  5019.5 2133.92  5027.7 2137.21  5041.7 2140.85  5050.1 2143.44
  5058.3 2144.54  5072.6 2145.69  5080.5 2146.95  5102.7 2148.43  5105.3 2149.23
#Mann=3,-1,0
  4872.0    0.16       0  4998.3    0.07       0  5002.3    0.16       0
Bank Sta=4998.3,5002.3
Exp/Cntr=0.3,0.1

Type RM Length L Ch R = 1,1072,52,52,52
BEGIN DESCRIPTION:
elmc512
END DESCRIPTION:
XS GIS Cut Line= 3
      1512685.65      6773684.80      1512796.35      6773638.14
      1512871.12      6773589.00
#Sta/Elev= 30
  4876.7 2158.22  4879.0 2158.22  4881.4 2156.86  4886.8 2154.86  4897.7 2153.39
  4905.1 2151.21  4910.5 2151.89  4928.8 2149.98  4934.3 2150.60  4941.1 2148.88
  4952.0 2144.19  4958.0 2139.45  4963.4 2139.28  4973.7 2130.95  4979.7 2120.51
  4979.9 2120.01  4983.4 2120.01  4983.7 2120.51  4987.1 2121.56  4993.4 2132.01
  4999.0 2132.01  5003.7 2138.91  5009.7 2141.34  5024.8 2142.83  5031.1 2142.35
  5039.8 2142.51  5045.8 2142.94  5076.0 2145.68  5082.0 2146.77  5086.3 2146.97
#Mann=3,-1,0
  4876.7    0.16       0  4979.7    0.07       0  4983.7    0.16       0
Bank Sta=4979.7,4983.7
Exp/Cntr=0.3,0.1