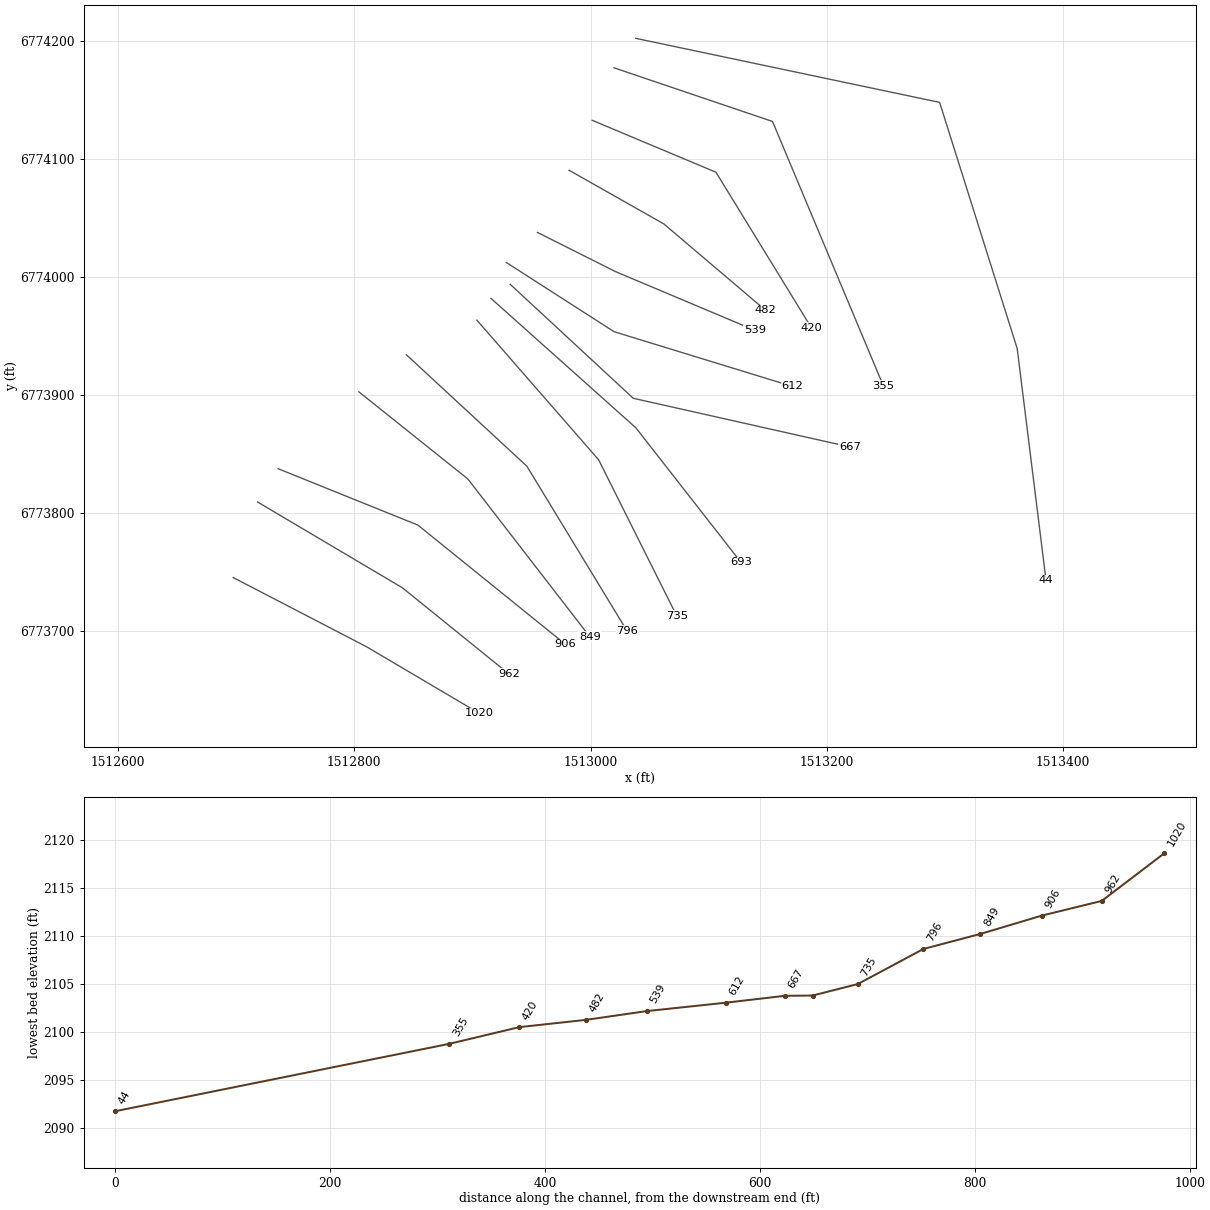
HEC-RAS study Elm 46.prj: Elm 46 Base Level Engineering

--- Elm 46.g01 (geometry) --- (continued)

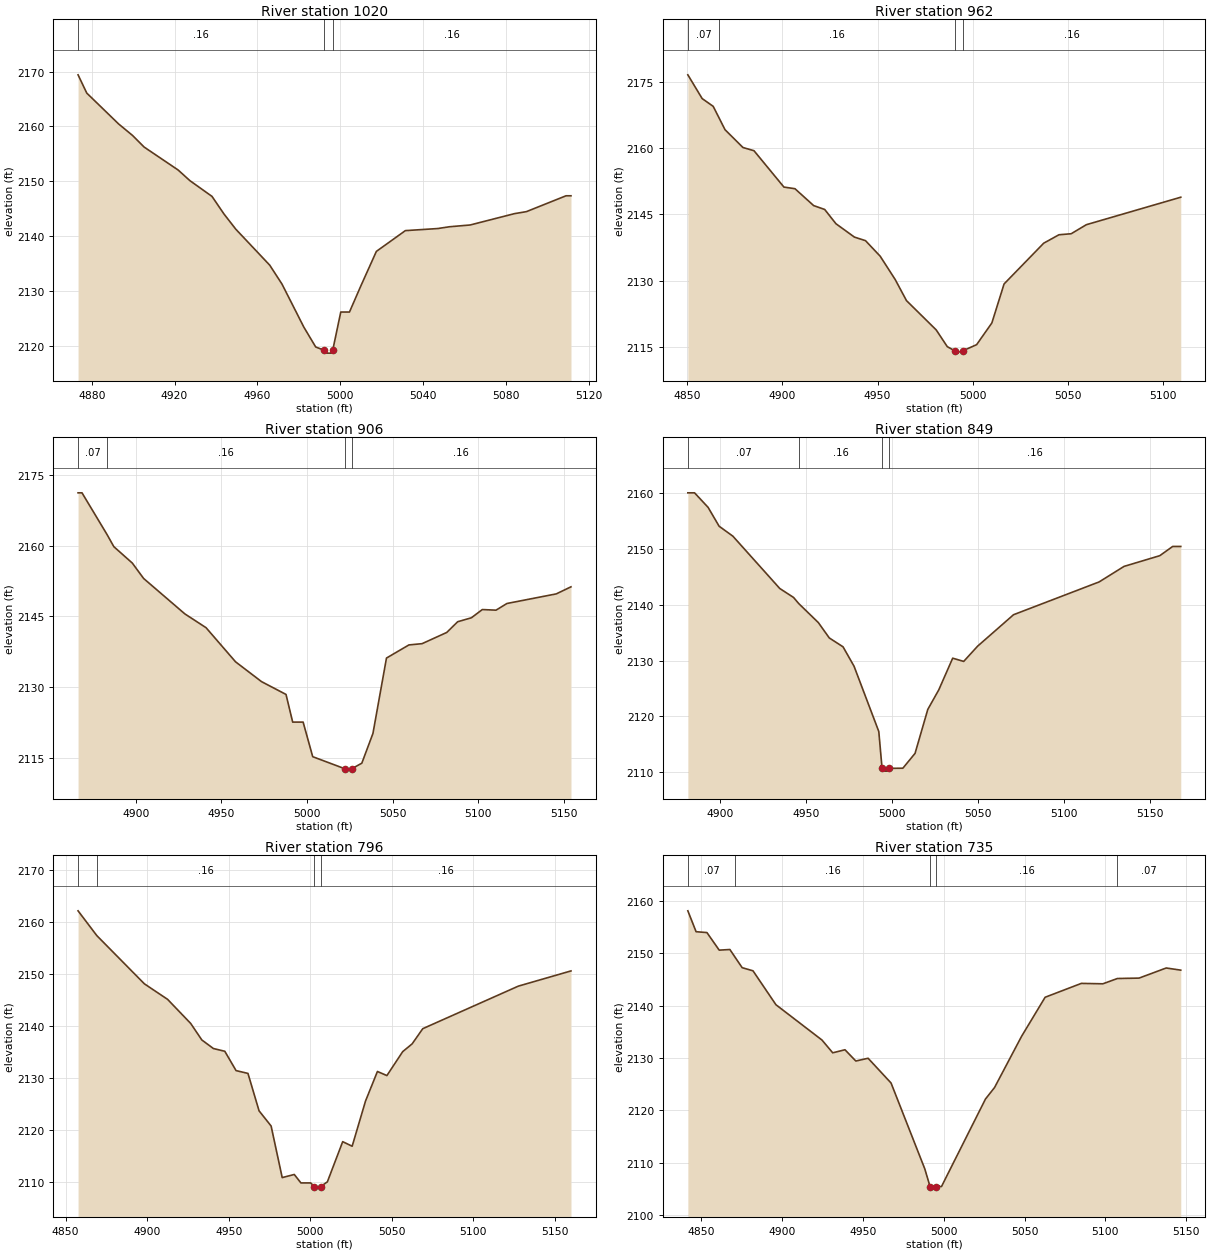
Type RM Length L Ch R = 1,1020,58,58,58
BEGIN DESCRIPTION:
elmc511
END DESCRIPTION:
XS GIS Cut Line= 3
      1512697.57      6773745.58      1512810.45      6773686.96
      1512905.93      6773630.54
#Sta/Elev= 30
  4873.4 2169.42  4877.6 2166.09  4893.0 2160.45  4899.7 2158.36  4905.3 2156.24
  4921.8 2152.03  4927.4 2150.11  4938.1 2147.23  4943.9 2144.01  4949.6 2141.24
  4966.0 2134.67  4971.9 2131.23  4982.5 2123.34  4988.2 2119.74  4992.4 2119.12
  4992.7 2118.62  4996.2 2118.62  4996.4 2119.12  5000.3 2126.12  5004.5 2126.12
  5010.0 2130.89  5017.5 2137.19  5031.5 2140.98  5047.1 2141.36  5052.9 2141.69
  5062.8 2142.01  5084.2 2144.08  5090.0 2144.45  5109.1 2147.34  5111.5 2147.34
#Mann=3,-1,0
  4873.4    0.16       0  4992.4    0.07       0  4996.4    0.16       0
Bank Sta=4992.4,4996.4
Exp/Cntr=0.3,0.1

Type RM Length L Ch R = 1,962,56,56,56
BEGIN DESCRIPTION:
elmc510
END DESCRIPTION:
XS GIS Cut Line= 3
      1512718.20      6773809.59      1512840.83      6773736.88
      1512931.02      6773663.87
#Sta/Elev= 30
  4850.5 2176.51  4858.0 2171.15  4863.8 2169.39  4866.9 2166.76  4870.0 2164.12
  4879.4 2160.10  4885.2 2159.37  4900.9 2151.16  4906.7 2150.79  4916.5 2146.98
  4922.3 2146.10  4928.2 2142.88  4937.9 2139.86  4943.7 2139.06  4951.4 2135.55
  4959.3 2130.27  4965.2 2125.52  4980.8 2118.90  4986.6 2115.13  4990.6 2114.16
  4990.8 2113.66  4994.6 2114.16  5002.0 2115.57  5010.0 2120.48  5016.4 2129.28
  5037.2 2138.49  5045.2 2140.39  5051.6 2140.62  5059.6 2142.67  5109.1 2148.87
#Mann=4,-1,0
  4850.5    0.07       0  4866.9    0.16       0  4990.6    0.07       0
  4994.6    0.16       0
Bank Sta=4990.6,4994.6
Exp/Cntr=0.3,0.1

Type RM Length L Ch R = 1,906,57,57,57
BEGIN DESCRIPTION:
elmc509
END DESCRIPTION:
XS GIS Cut Line= 3
      1512735.61      6773837.78      1512853.86      6773790.05
      1512978.64      6773689.13
#Sta/Elev= 30
  4866.2 2171.27  4868.5 2171.27  4883.1 2162.43  4887.1 2159.83  4897.9 2156.34
  4904.5 2153.07  4928.6 2145.54  4941.0 2142.60  4958.2 2135.36  4973.4 2131.14
  4987.7 2128.42  4991.6 2122.54  4997.7 2122.54  5003.3 2115.19  5022.1 2112.62
  5022.3 2112.12  5026.1 2112.62  5032.0 2113.81  5038.5 2120.14  5046.4 2136.15
  5059.5 2138.94  5067.2 2139.21  5081.6 2141.59  5088.0 2143.87  5096.0 2144.71
  5102.4 2146.46  5110.4 2146.33  5116.8 2147.75  5145.6 2149.79  5154.2 2151.29
#Mann=4,-1,0
  4866.2    0.07       0  4883.1    0.16       0  5022.1    0.07       0
  5026.1    0.16       0
Bank Sta=5022.1,5026.1
Exp/Cntr=0.3,0.1

Type RM Length L Ch R = 1,849,53,53,53
BEGIN DESCRIPTION:
elmc508
END DESCRIPTION:
XS GIS Cut Line= 3
      1512803.91      6773902.92      1512896.17      6773829.11
      1512999.26      6773695.64
#Sta/Elev= 30
  4881.1 2160.03  4885.0 2160.03  4892.9 2157.42  4899.3 2154.05  4907.3 2152.27
  4934.6 2142.90  4942.6 2141.30  4945.7 2140.18  4957.0 2136.81  4963.4 2134.05
  4971.4 2132.46  4977.8 2128.99  4992.2 2117.30  4994.1 2110.71  4994.4 2110.21
  4997.9 2110.21  4998.1 2110.71  5006.2 2110.73  5013.3 2113.39  5020.7 2121.25
  5027.1 2124.76  5035.2 2130.43  5041.6 2129.85  5049.7 2132.58  5070.6 2138.21
  5120.4 2144.08  5134.9 2146.86  5155.7 2148.78  5163.2 2150.43  5167.9 2150.43
#Mann=4,-1,0
  4881.1    0.07       0  4945.7    0.16       0  4994.1    0.07       0
  4998.1    0.16       0
Bank Sta=4994.1,4998.1
Exp/Cntr=0.3,0.1

Type RM Length L Ch R = 1,796,61,61,61
BEGIN DESCRIPTION:
elmc507
END DESCRIPTION:
XS GIS Cut Line= 3
      1512844.11      6773934.34      1512946.09      6773839.96
      1513030.92      6773700.36
#Sta/Elev= 30
  4857.6 2162.22  4869.1 2157.45  4898.3 2148.16  4912.5 2145.18  4926.7 2140.53
  4933.5 2137.36  4940.6 2135.71  4947.6 2135.18  4954.5 2131.46  4961.8 2130.92
  4968.6 2123.72  4976.0 2120.79  4982.8 2110.86  4990.2 2111.46  4994.3 2109.83
  5000.3 2109.83  5002.4 2109.14  5002.6 2108.64  5006.4 2109.14  5010.5 2110.04
  5019.9 2117.78  5025.7 2116.90  5033.9 2125.60  5041.2 2131.29  5047.0 2130.50
  5056.7 2135.11  5062.5 2136.61  5069.0 2139.53  5127.6 2147.72  5159.9 2150.65
#Mann=4,-1,0
  4857.6    0.07       0  4869.1    0.16       0  5002.4    0.07       0
  5006.4    0.16       0
Bank Sta=5002.4,5006.4
Exp/Cntr=0.3,0.1

Type RM Length L Ch R = 1,735,42,42,42
BEGIN DESCRIPTION:
elmc506
END DESCRIPTION:
XS GIS Cut Line= 3
      1512903.79      6773963.63      1513006.85      6773845.38
      1513073.06      6773712.97
#Sta/Elev= 30
  4841.7 2158.14  4846.8 2154.15  4853.5 2153.99  4861.1 2150.63  4867.7 2150.75
  4871.0 2149.24  4875.3 2147.28  4882.0 2146.68  4896.2 2140.20  4924.7 2133.45
  4931.3 2131.02  4938.9 2131.60  4945.6 2129.45  4953.2 2129.98  4967.4 2125.25
  4988.3 2108.82  4991.5 2105.48  4991.8 2104.98  4995.5 2105.48  4998.6 2105.48
  5025.8 2122.19  5031.4 2124.38  5048.1 2134.15  5062.7 2141.63  5085.1 2144.28
  5098.4 2144.20  5107.4 2145.21  5120.8 2145.29  5137.6 2147.22  5146.6 2146.81
#Mann=5,-1,0
  4841.7    0.07       0  4871.0    0.16       0  4991.5    0.07       0
  4995.5    0.16       0  5107.4    0.07       0
Bank Sta=4991.5,4995.5
Exp/Cntr=0.3,0.1

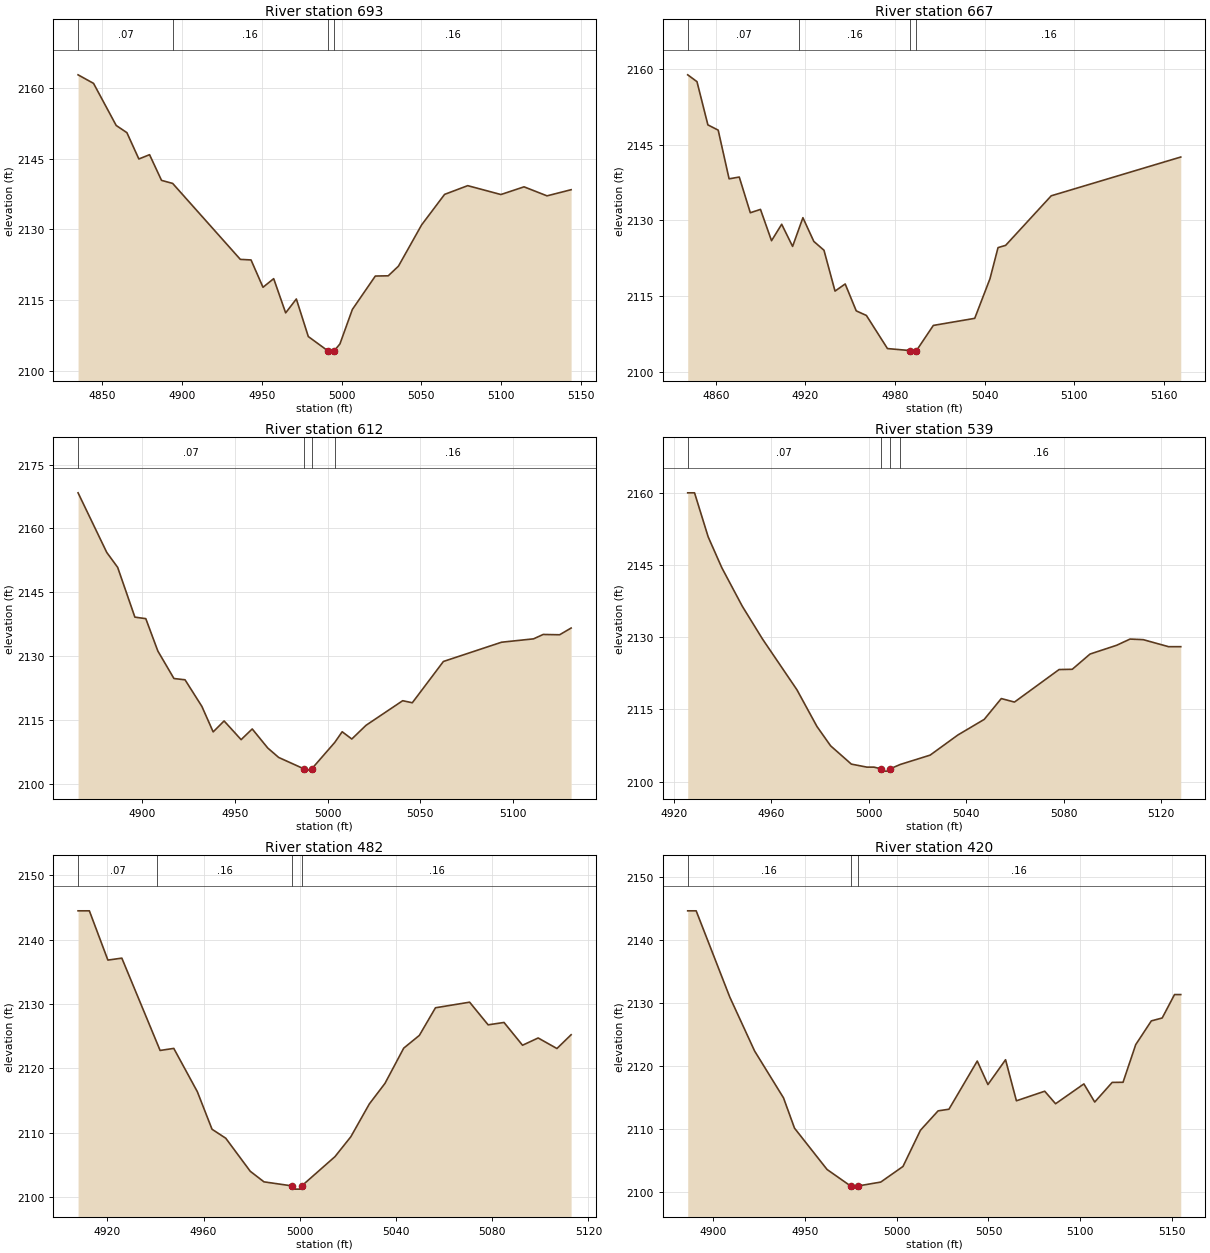
Type RM Length L Ch R = 1,693,26,26,26
BEGIN DESCRIPTION:
elmc503
END DESCRIPTION:
XS GIS Cut Line= 3
      1512915.70      6773982.11      1513038.32      6773872.51
      1513127.28      6773758.59
#Sta/Elev= 30
  4834.9 2162.74  4844.6 2160.93  4858.8 2152.01  4865.5 2150.49  4873.0 2144.91
  4879.7 2145.82  4887.2 2140.38  4894.2 2139.73  4936.6 2123.64  4943.3 2123.52
  4950.8 2117.73  4957.5 2119.56  4965.0 2112.31  4971.7 2115.25  4979.2 2107.29
  4991.4 2104.28  4991.7 2103.78  4995.4 2104.28  4999.0 2105.72  5006.8 2113.03
  5021.2 2120.11  5029.3 2120.16  5035.7 2122.21  5050.2 2130.94  5064.6 2137.41
  5079.1 2139.26  5099.9 2137.38  5114.4 2139.01  5128.8 2137.10  5143.9 2138.40
#Mann=4,-1,0
  4834.9    0.07       0  4894.2    0.16       0  4991.4    0.07       0
  4995.4    0.16       0
Bank Sta=4991.4,4995.4
Exp/Cntr=0.3,0.1

Type RM Length L Ch R = 1,667,55,55,55
BEGIN DESCRIPTION:
elmc504
END DESCRIPTION:
XS GIS Cut Line= 3
      1512932.01      6773994.01      1513036.15      6773897.47
      1513219.56      6773856.23
#Sta/Elev= 30
  4841.2 2158.80  4847.4 2157.45  4854.7 2148.90  4861.6 2147.86  4868.9 2138.23
  4875.7 2138.58  4883.1 2131.52  4889.9 2132.18  4897.3 2125.99  4904.1 2129.24
  4911.4 2124.86  4915.8 2128.48  4918.3 2130.54  4925.6 2125.85  4932.4 2124.10
  4939.8 2116.02  4946.6 2117.43  4954.0 2112.11  4960.8 2111.20  4974.9 2104.65
  4990.3 2104.25  4990.5 2103.75  4994.3 2104.25  5005.6 2109.23  5033.3 2110.63
  5043.5 2118.46  5048.9 2124.62  5054.0 2125.07  5084.5 2134.87  5171.2 2142.54
#Mann=4,-1,0
  4841.2    0.07       0  4915.8    0.16       0  4990.3    0.07       0
  4994.3    0.16       0
Bank Sta=4990.3,4994.3
Exp/Cntr=0.3,0.1

Type RM Length L Ch R = 1,612,73,73,73
BEGIN DESCRIPTION:
elmc505
END DESCRIPTION:
XS GIS Cut Line= 3
      1512928.71      6774012.50      1513019.87      6773953.89
      1513170.93      6773907.50
#Sta/Elev= 30
  4865.2 2168.36  4880.7 2154.37  4886.6 2150.86  4895.9 2139.18  4901.8 2138.82
  4908.3 2131.23  4917.0 2124.77  4923.0 2124.47  4932.1 2118.22  4938.2 2112.24
  4944.1 2114.81  4953.3 2110.42  4959.3 2112.93  4967.7 2108.45  4973.6 2106.24
  4987.4 2103.53  4987.7 2103.03  4991.4 2103.53  5003.9 2109.77  5007.9 2112.27
  5013.1 2110.57  5020.8 2113.79  5040.6 2119.56  5045.8 2119.08  5062.6 2128.77
  5094.0 2133.29  5111.3 2134.08  5116.5 2135.11  5125.4 2135.04  5131.6 2136.62
#Mann=4,-1,0
  4865.2    0.07       0  4987.4    0.07       0  4991.4    0.07       0
  5003.9    0.16       0
Bank Sta=4987.4,4991.4
Exp/Cntr=0.3,0.1

Type RM Length L Ch R = 1,539,57,57,57
BEGIN DESCRIPTION:
elmc396
END DESCRIPTION:
XS GIS Cut Line= 3
      1512954.99      6774038.00      1513021.30      6774004.70
      1513139.24      6773954.97
#Sta/Elev= 30
  4925.8 2159.99  4928.6 2159.99  4934.2 2150.83  4939.8 2144.41  4948.2 2136.41
  4956.5 2129.59  4970.6 2119.06  4978.8 2111.44  4984.4 2107.42  4992.9 2103.62
  4999.3 2102.99  5002.2 2102.99  5004.9 2102.66  5005.2 2102.16  5008.7 2102.16
  5008.9 2102.66  5013.0 2103.55  5025.2 2105.48  5036.6 2109.67  5047.4 2112.91
  5054.4 2117.24  5059.8 2116.51  5078.1 2123.27  5083.5 2123.32  5090.8 2126.49
  5101.7 2128.31  5107.2 2129.60  5112.6 2129.48  5123.0 2128.02  5128.0 2128.02
#Mann=4,-1,0
  4925.8    0.07       0  5004.9    0.07       0  5008.9    0.07       0
  5013.0    0.16       0
Bank Sta=5004.9,5008.9
Exp/Cntr=0.3,0.1

Type RM Length L Ch R = 1,482,62,62,62
BEGIN DESCRIPTION:
elmc502
END DESCRIPTION:
XS GIS Cut Line= 3
      1512981.85      6774090.63      1513062.06      6774045.17
      1513148.00      6773972.10
#Sta/Elev= 30
  4907.8 2144.47  4912.5 2144.47  4920.2 2136.82  4926.0 2137.12  4940.8 2123.79
  4941.9 2122.78  4947.6 2123.10  4957.4 2116.37  4963.5 2110.54  4969.2 2109.15
  4979.4 2104.01  4985.1 2102.37  4996.8 2101.74  4997.1 2101.24  5000.6 2101.24
  5000.8 2101.74  5014.6 2106.28  5021.2 2109.37  5028.9 2114.47  5035.4 2117.66
  5043.2 2123.14  5049.7 2125.12  5056.4 2129.41  5070.6 2130.28  5078.3 2126.76
  5084.9 2127.13  5092.6 2123.59  5099.1 2124.72  5106.9 2123.08  5112.8 2125.22
#Mann=4,-1,0
  4907.8    0.07       0  4940.8    0.16       0  4996.8    0.07       0
  5000.8    0.16       0
Bank Sta=4996.8,5000.8
Exp/Cntr=0.3,0.1

Type RM Length L Ch R = 1,420,65,65,65
BEGIN DESCRIPTION:
elmc501
END DESCRIPTION:
XS GIS Cut Line= 3
      1513001.43      6774132.93      1513106.17      6774088.95
      1513186.97      6773957.15
#Sta/Elev= 30
  4886.4 2144.68  4891.0 2144.68  4909.3 2130.97  4922.8 2122.41  4938.5 2114.98
  4944.5 2110.16  4962.2 2103.60  4975.0 2100.98  4975.3 2100.48  4979.0 2100.98
  4991.4 2101.60  5003.5 2104.08  5013.0 2109.83  5022.6 2112.91  5028.5 2113.17
  5043.9 2120.82  5049.7 2117.09  5059.3 2121.03  5065.2 2114.51  5080.6 2116.03
  5086.5 2114.04  5101.9 2117.19  5107.8 2114.31  5117.3 2117.43  5123.2 2117.45
  5130.1 2123.43  5138.6 2127.20  5144.5 2127.66  5151.2 2131.38  5154.6 2131.38
#Mann=3,-1,0
  4886.4    0.16       0  4975.0    0.07       0  4979.0    0.16       0
Bank Sta=4975,4979
Exp/Cntr=0.3,0.1

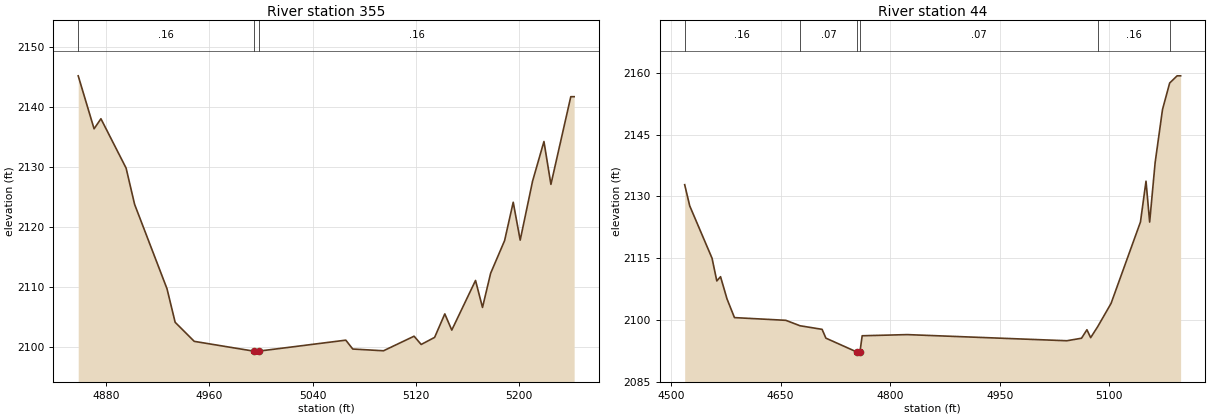
Type RM Length L Ch R = 1,355,311,311,311
BEGIN DESCRIPTION:
elmc500
END DESCRIPTION:
XS GIS Cut Line= 3
      1513019.82      6774177.43      1513154.03      6774131.95
      1513247.75      6773908.29
#Sta/Elev= 30
  4858.3 2145.17  4870.6 2136.33  4875.9 2138.01  4895.4 2129.78  4902.0 2123.72
  4927.1 2109.64  4933.4 2104.05  4948.2 2100.87  4994.2 2099.24  4994.5 2098.74
  4998.2 2099.24  5065.6 2101.07  5071.0 2099.59  5094.8 2099.30  5118.5 2101.73
  5124.0 2100.35  5134.4 2101.53  5142.3 2105.45  5147.7 2102.75  5166.1 2111.03
  5171.5 2106.53  5177.8 2112.23  5188.6 2117.67  5195.3 2124.08  5200.7 2117.76
  5210.3 2127.61  5219.1 2134.21  5224.5 2127.06  5239.9 2141.69  5242.5 2141.69
#Mann=3,-1,0
  4858.3    0.16       0  4994.2    0.07       0  4998.2    0.16       0
Bank Sta=4994.2,4998.2
Exp/Cntr=0.3,0.1

Type RM Length L Ch R = 1,44,0,0,0
BEGIN DESCRIPTION:
elmc499
END DESCRIPTION:
XS GIS Cut Line= 4
      1513038.28      6774202.38      1513295.48      6774148.12
      1513361.13      6773939.67      1513385.54      6773743.38
#Sta/Elev= 30
  4518.6 2132.85  4525.5 2127.71  4556.1 2114.98  4562.6 2109.48  4567.7 2110.51
  4576.6 2105.10  4586.8 2100.57  4657.1 2099.91  4676.6 2098.59  4706.8 2097.72
  4712.0 2095.58  4754.6 2092.20  4754.9 2091.70  4758.6 2092.20  4761.7 2096.16
  4823.5 2096.44  5042.0 2094.95  5062.1 2095.56  5069.5 2097.62  5074.6 2095.70
  5084.4 2098.42  5102.5 2104.00  5142.8 2123.79  5150.4 2133.70  5155.4 2123.77
  5162.9 2138.22  5173.0 2151.12  5182.8 2157.54  5193.0 2159.29  5197.8 2159.29
#Mann=6,-1,0
  4518.6    0.16       0  4676.6    0.07       0  4754.6    0.07       0
  4758.6    0.07       0  5084.4    0.16       0  5182.8    0.07       0
Bank Sta=4754.6,4758.6
Exp/Cntr=0.3,0.1

Chan Stop Cuts=-1