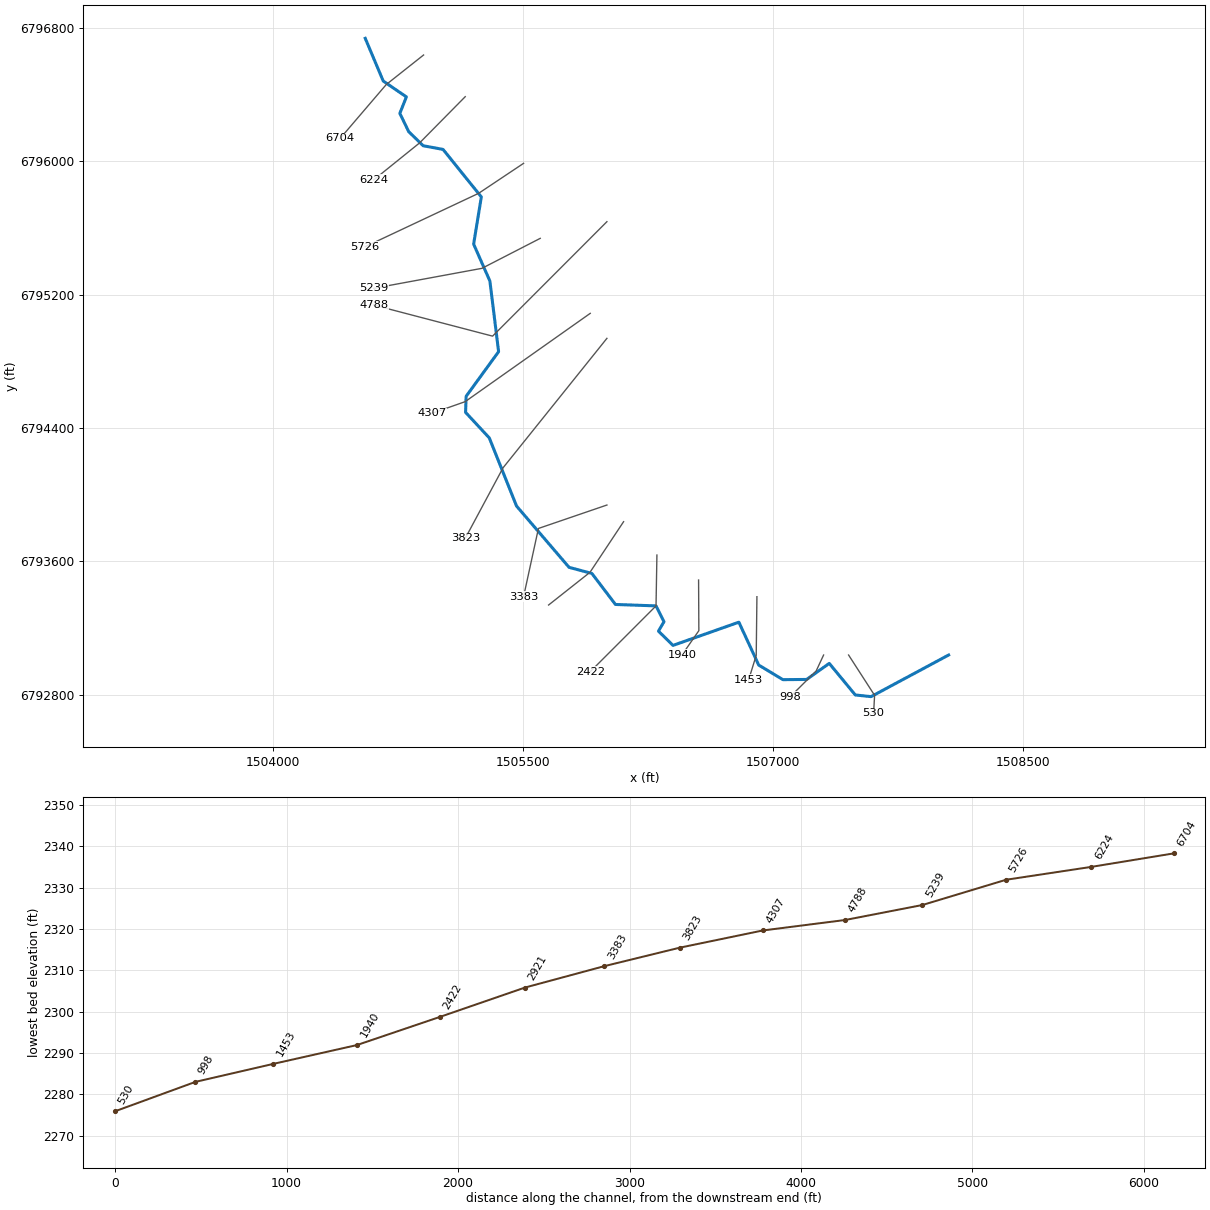
--- Elm 47.prj (project) ---

Proj Title=Elm 47 Base Level Engineering
Current Plan=p01
Default Exp/Contr=0.3,0.1
English Units
Geom File=g01
Flow File=f01
Plan File=p01
Y Axis Title=Elevation
X Axis Title(PF)=Main Channel Distance
X Axis Title(XS)=Station
BEGIN DESCRIPTION:
Elm 47
END DESCRIPTION:
DSS Export Rating Curves= 0
DSS Export Rating Curve Sorted= 0
DSS Export Volume Flow Curves= 0
DXF OffsetX= 0
DXF OffsetY= 0
DXF ScaleX= 1
DXF ScaleY= 10

--- Elm 47.p01 (plan) ---

Plan Title=Multiple Run
Short Identifier=Multiple
Geom File=g01
Flow File=f01
Subcritical Flow
K Sum by GR= 0
Std Step Tol= 0.01
Critical Tol= 0.01
Num of Std Step Trials= 20
Max Error Tol= 0.3
Flow Tol Ratio= 0.001
Split Flow NTrial= 30
Split Flow Tol= 0.02
Split Flow Ratio= 0.02
Log Output Level= 0
Friction Slope Method= 1
Unsteady Friction Slope Method= 2
Unsteady Bridges Friction Slope Method= 1
Parabolic Critical Depth
Global Vel Dist=  1 , 1 , 1
Global Log Level= 0
CheckData=True
Encroach Param= -1, 0, 0, 0
BEGIN DESCRIPTION:
Multiple Run
END DESCRIPTION:

--- Elm 47.f01 (steady flow) ---

Flow Title=Multiple
Number of Profiles=7
Profile Names=10-year,25-year,50-year,1pct_min,100-year,1pct_plu,500-year
River Rch & RM= Elm 47,Reach-1,6704
     340     485     608     472     756    1040    1190
River Rch & RM= Elm 47,Reach-1,5239
     452     651     823     644    1030    1420    1640
Boundary for River Rch & Prof#=Elm 47,Reach-1,1
Up Type=0
Dn Type=3
Dn Slope=0.005
Boundary for River Rch & Prof#=Elm 47,Reach-1,2
Up Type=0
Dn Type=3
Dn Slope=0.005
Boundary for River Rch & Prof#=Elm 47,Reach-1,3
Up Type=0
Dn Type=3
Dn Slope=0.005
Boundary for River Rch & Prof#=Elm 47,Reach-1,4
Up Type=0
Dn Type=3
Dn Slope=0.005
Boundary for River Rch & Prof#=Elm 47,Reach-1,5
Up Type=0
Dn Type=3
Dn Slope=0.005
Boundary for River Rch & Prof#=Elm 47,Reach-1,6
Up Type=0
Dn Type=3
Dn Slope=0.005
Boundary for River Rch & Prof#=Elm 47,Reach-1,7
Up Type=0
Dn Type=3
Dn Slope=0.005

--- Elm 47.g01 (geometry) ---

Geom Title=Existing Conditions
Program Version=4.10

River Reach=Elm 47          ,Reach-1
Reach XY= 30
        1504555.        6796738.      1504663.02      6796481.66
      1504801.93      6796386.57      1504762.56        6796288.
      1504815.74       6796178.3      1504902.56      6796093.52
      1505021.79      6796071.56      1505251.47      6795786.53
      1505205.38      6795503.27      1505302.74      6795282.06
      1505355.22       6794858.2       1505160.4      6794590.43
      1505156.96      6794493.89      1505299.48      6794340.43
      1505462.86      6793931.83      1505777.85      6793564.18
      1505914.81      6793527.49      1506056.25      6793341.45
      1506299.62      6793332.82      1506347.24      6793237.94
       1506314.3      6793181.29      1506401.56      6793095.77
      1506796.68      6793235.03      1506915.63        6792978.
      1507060.93      6792890.23      1507203.53      6792891.54
      1507338.96      6792987.83      1507495.21      6792798.43
      1507589.72      6792788.38        1508055.        6793038.

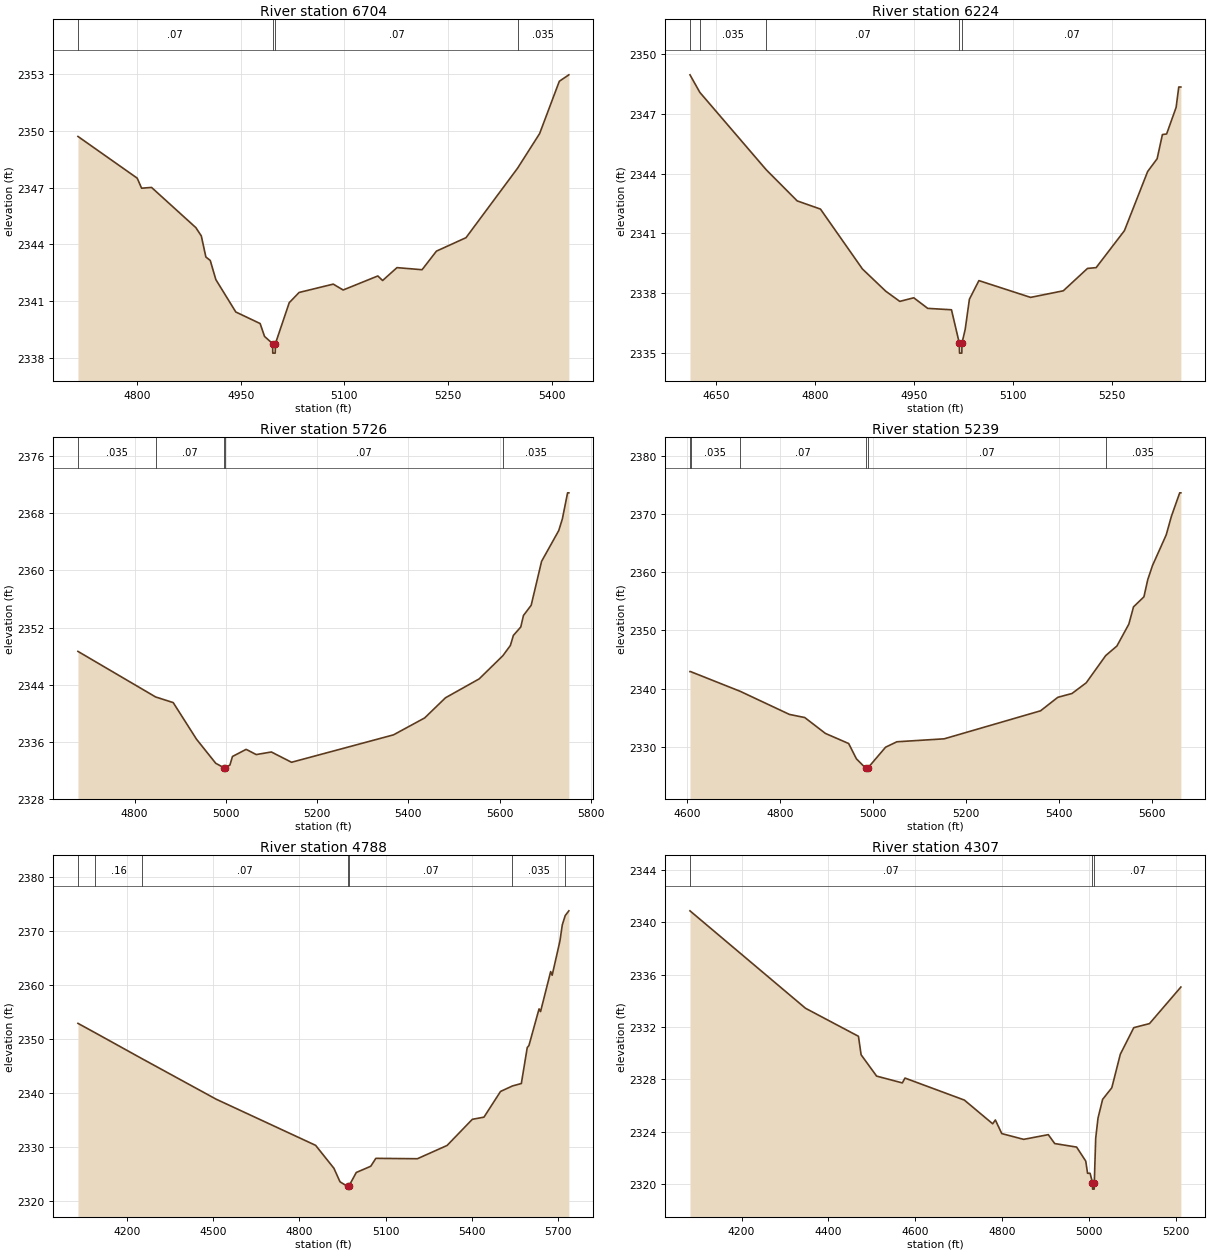
Type RM Length L Ch R = 1 ,6704    ,480,480,480
BEGIN DESCRIPTION:
284
END DESCRIPTION:
XS GIS Cut Line= 3
      1504904.96      6796637.97      1504681.17      6796460.86
      1504404.98      6796137.97
#Sta/Elev= 30
  4714.6  2349.7  4800.3  2347.5  4806.7 2346.97  4821.1 2347.01  4885.2 2344.89
  4893.1 2344.45  4899.7 2343.34    4906 2343.16  4914.1 2342.15    4943 2340.44
  4978.2 2339.83  4984.6 2339.15  4996.3 2338.77  4996.5 2338.27    5000 2338.27
  5000.3 2338.77  5020.3 2340.93  5034.6 2341.47    5084 2341.91  5098.3  2341.6
  5148.5 2342.34  5155.4  2342.1  5176.2 2342.78  5212.5 2342.67  5233.3 2343.65
  5276.1 2344.36  5350.8 2348.03  5382.6 2349.85  5411.1 2352.61  5424.9 2352.95
#Mann= 4 ,-1 , 0
  4714.6     .07       0  4996.3     .07       0  5000.3     .07       0
  5350.8    .035       0
Bank Sta=4996.3,5000.3
XS Rating Curve= 0 ,0
Exp/Cntr=0.3,0.1

Type RM Length L Ch R = 1 ,6224    ,498,498,498
BEGIN DESCRIPTION:
283
END DESCRIPTION:
XS GIS Cut Line= 3
      1505154.98      6796387.98      1504881.43      6796110.86
      1504604.98      6795887.98
#Sta/Elev= 30
  4610.6 2348.94  4625.6 2348.06  4726.2 2344.19  4773.2 2342.63  4808.5 2342.22
  4872.2 2339.22  4907.5 2338.11  4928.8  2337.6    4950 2337.78  4971.2 2337.25
  5007.2 2337.18  5019.1 2335.51  5019.4 2335.01  5022.9 2335.01  5023.1 2335.51
    5028  2336.2  5034.4 2337.71  5048.8 2338.64  5127.2  2337.8  5176.8 2338.13
  5213.5 2339.25  5226.6 2339.29  5269.5 2341.14  5304.7  2344.1  5319.1 2344.74
  5327.1 2345.95  5333.5 2345.98  5347.9 2347.31  5351.9 2348.33  5355.1 2348.33
#Mann= 5 ,-1 , 0
  4610.6     .07       0  4625.6    .035       0  4726.2     .07       0
  5019.1     .07       0  5023.1     .07       0
Bank Sta=5019.1,5023.1
XS Rating Curve= 0 ,0
Exp/Cntr=0.3,0.1

Type RM Length L Ch R = 1 ,5726    ,487,487,487
BEGIN DESCRIPTION:
282
END DESCRIPTION:
XS GIS Cut Line= 3
      1505505.02      6795988.01       1505235.4      6795808.16
      1504554.96      6795487.98
#Sta/Elev= 30
  4675.9 2348.66  4846.1 2342.28  4884.7 2341.49  4935.8 2336.36  4977.9 2332.99
  4995.2 2332.39  4995.5 2331.89    4999 2331.89  4999.2 2332.39    5009 2332.74
  5014.6 2333.94  5044.6 2334.94  5066.7 2334.21  5099.9 2334.57  5144.1 2333.13
  5367.6 2336.97  5435.9 2339.34  5481.5 2342.16  5555.4 2344.81  5607.4 2348.06
  5623.8 2349.49  5630.4  2350.9  5646.6 2352.08  5652.5 2353.69  5669.4 2355.12
  5692.2 2361.27  5729.9 2365.59  5737.8 2367.23  5749.2 2370.87    5752 2370.87
#Mann= 5 ,-1 , 0
  4675.9    .035       0  4846.1     .07       0  4995.2     .07       0
  4999.2     .07       0  5607.4    .035       0
Bank Sta=4995.2,4999.2
XS Rating Curve= 0 ,0
Exp/Cntr=0.3,0.1

Type RM Length L Ch R = 1 ,5239    ,451,451,451
BEGIN DESCRIPTION:
281
END DESCRIPTION:
XS GIS Cut Line= 3
      1505604.99      6795537.99      1505255.24       6795358.1
      1504605.04      6795238.01
#Sta/Elev= 30
  4606.7 2342.92  4607.9 2342.92  4714.7 2339.52  4820.3 2335.55  4853.3 2335.01
  4897.6 2332.28  4947.6 2330.54  4964.2 2327.91  4984.3 2326.29  4984.5 2325.79
  4988.1 2325.79  4988.4 2326.29  5026.9 2329.91  5051.1 2330.84  5152.8 2331.35
  5359.8 2336.17  5396.8 2338.49  5427.3 2339.15  5457.9 2340.99  5499.7 2345.67
  5523.8 2347.32  5549.4 2351.08  5559.5 2354.06  5581.8 2355.78  5590.1 2358.75
  5600.2 2361.16  5629.7 2366.44  5640.9 2369.65  5658.7 2373.68  5661.2 2373.68
#Mann= 6 ,-1 , 0
  4606.7     .07       0  4607.9    .035       0  4714.7     .07       0
  4984.3     .07       0  4988.4     .07       0  5499.7    .035       0
Bank Sta=4984.3,4988.4
XS Rating Curve= 0 ,0
Exp/Cntr=0.3,0.1

Type RM Length L Ch R = 1 ,4788    ,481,481,481
BEGIN DESCRIPTION:
280
END DESCRIPTION:
XS GIS Cut Line= 3
      1506005.02      6795638.02      1505319.03      6794951.23
      1504604.96      6795138.01
#Sta/Elev= 30
  4029.3 2352.86  4089.8  2351.1  4250.8 2346.36  4510.2 2338.82  4856.6 2330.27
  4920.3 2326.02  4941.5 2323.52  4967.7 2322.66    4968 2322.16  4971.8 2322.66
  4998.1 2325.24  5048.6  2326.4  5066.2 2327.86  5210.9 2327.79  5314.3 2330.25
  5402.1 2335.09  5442.6 2335.49  5500.3 2340.25  5541.9 2341.27  5572.7 2341.72
  5593.3 2348.38  5599.1 2348.75  5634.4 2355.54  5639.6 2355.04  5674.8 2362.45
    5680 2361.77    5707  2368.1  5715.3 2371.11  5725.4 2372.81  5738.1  2373.7
#Mann= 7 ,-1 , 0
  4029.3     .07       0  4089.8     .16       0  4250.8     .07       0
  4967.7     .07       0  4971.8     .07       0  5541.9    .035       0
  5725.4     .07       0
Bank Sta=4967.7,4971.8
XS Rating Curve= 0 ,0
Exp/Cntr=0.3,0.1

Type RM Length L Ch R = 1 ,4307    ,484,484,484
BEGIN DESCRIPTION:
279
END DESCRIPTION:
XS GIS Cut Line= 3
      1505905.01      6795088.01      1505154.32      6794558.08
      1504954.98      6794487.99
#Sta/Elev= 30
  4081.1 2340.87  4347.1 2333.43    4469 2331.29  4475.1 2329.88  4510.8 2328.25
    4570 2327.73  4576.1  2328.1  4712.8 2326.42    4778 2324.61  4784.2  2324.9
    4799 2323.86  4849.4 2323.42  4906.1 2323.78  4920.8  2323.1  4971.3 2322.83
  4992.3 2321.76  4996.5 2320.83  5002.3 2320.83  5007.8 2320.12  5008.1 2319.62
  5011.7 2319.62    5012 2320.12  5015.2  2323.5  5020.5 2325.04  5031.1 2326.47
  5052.3 2327.36  5071.9 2329.92  5102.9 2331.95  5139.1 2332.26  5211.3 2335.05
#Mann= 3 ,-1 , 0
  4081.1     .07       0  5007.8     .07       0    5012     .07       0
Bank Sta=5007.8,5012
XS Rating Curve= 0 ,0
Exp/Cntr=0.3,0.1

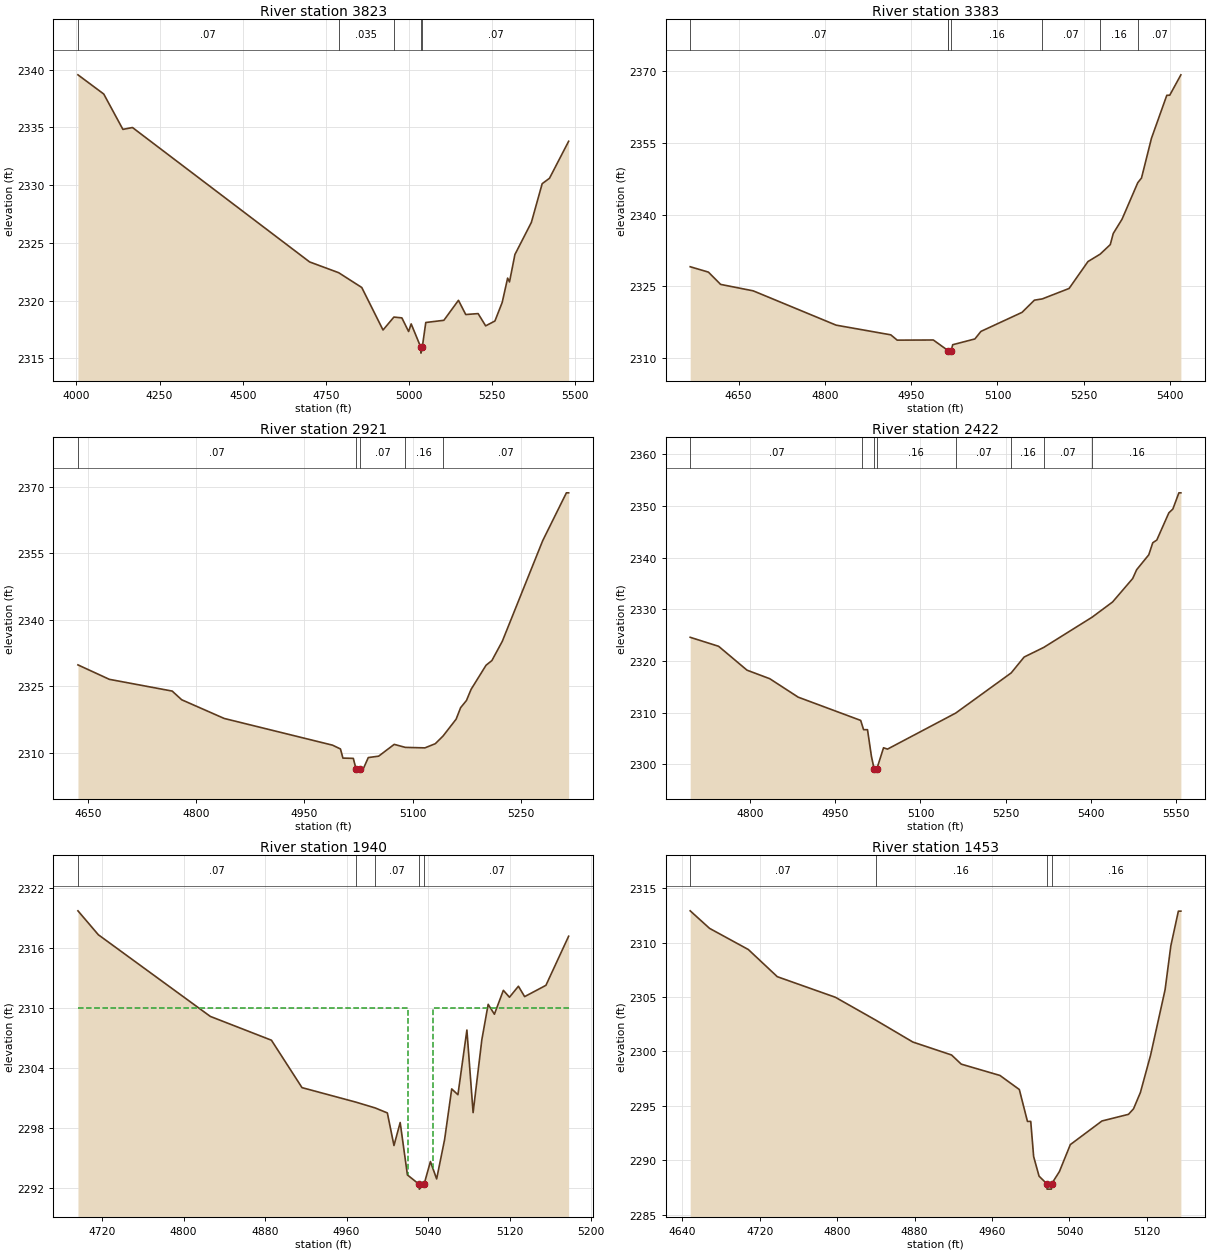
Type RM Length L Ch R = 1 ,3823    ,440,440,440
BEGIN DESCRIPTION:
278
END DESCRIPTION:
XS GIS Cut Line= 3
      1506004.99      6794937.99      1505381.94      6794161.45
      1505155.01      6793738.02
#Sta/Elev= 30
  4004.4 2339.54    4082 2337.88  4139.6 2334.82  4168.4 2334.98  4701.3 2323.35
  4788.6 2322.42  4858.1 2321.14  4922.1 2317.46  4954.8 2318.58  4978.8 2318.51
    4999 2317.33  5006.8 2317.99  5035.8 2315.96  5036.1 2315.46  5040.1 2315.96
  5050.7 2318.11  5105.1  2318.3    5149 2320.03  5170.9  2318.8  5208.1 2318.88
  5230.8 2317.82  5258.7 2318.24  5280.6 2319.85  5296.9 2321.95  5302.5 2321.62
  5318.8 2323.99  5368.3 2326.77  5400.8 2330.12  5422.8 2330.59  5480.4 2333.79
#Mann= 5 ,-1 , 0
  4004.4     .07       0  4788.6    .035       0  4954.8     .07       0
  5035.8     .07       0  5040.1     .07       0
Bank Sta=5035.8,5040.1
XS Rating Curve= 0 ,0
Exp/Cntr=0.3,0.1

Type RM Length L Ch R = 1 ,3383    ,462,462,462
BEGIN DESCRIPTION:
277
END DESCRIPTION:
XS GIS Cut Line= 3
      1506005.03      6793938.01      1505594.11      6793797.42
        1505505.        6793388.
#Sta/Elev= 30
  4565.7 2329.08  4597.4 2327.95  4618.6 2325.38  4675.3 2324.03  4819.4 2316.85
  4914.5 2314.82  4925.7 2313.71  4988.5 2313.74  5014.4  2311.5  5014.5 2311.49
  5014.9 2310.99  5019.5 2311.49  5022.2 2312.75  5060.8 2313.96  5071.3 2315.54
  5142.7 2319.52  5164.3 2322.08  5177.9 2322.34  5224.6 2324.53  5257.4 2330.16
  5278.7 2331.72  5296.2 2333.71  5301.4 2336.04  5316.7 2339.04  5344.1 2346.69
  5350.5 2347.65  5367.8 2355.96  5394.5 2364.97  5399.6 2364.99    5419 2369.26
#Mann= 7 ,-1 , 0
  4565.7     .07       0  5014.4     .16       0  5014.5     .07       0
  5019.5     .16       0  5177.9     .07       0  5278.7     .16       0
  5344.1     .07       0
Bank Sta=5014.5,5019.5
XS Rating Curve= 0 ,0
Exp/Cntr=0.3,0.1

Type RM Length L Ch R = 1 ,2921    ,499,499,499
BEGIN DESCRIPTION:
276
END DESCRIPTION:
XS GIS Cut Line= 3
      1506105.01      6793838.01      1505903.51      6793534.39
      1505655.03      6793338.03
#Sta/Elev= 30
  4635.6  2329.8  4679.2 2326.54  4766.4 2323.89  4779.6 2321.93  4838.6 2317.71
    4989 2311.68    5000 2310.82  5003.4 2308.76  5017.8  2308.7  5021.6 2306.32
    5022 2305.82  5026.7 2306.32  5032.2 2306.54  5038.6 2308.88    5053  2309.2
  5074.6 2311.86    5090 2311.18  5117.2 2311.07  5131.6 2312.01  5142.3 2313.73
  5160.5 2317.54  5166.8 2320.15  5174.9 2321.77  5181.3 2324.28  5202.1 2329.73
  5210.2 2330.78  5224.6 2335.12  5280.7 2357.84  5313.6 2368.64  5316.7 2368.64
#Mann= 5 ,-1 , 0
  4635.6     .07       0  5021.6     .07       0  5026.7     .07       0
    5090     .16       0  5142.3     .07       0
Bank Sta=5021.6,5026.7
XS Rating Curve= 0 ,0
Exp/Cntr=0.3,0.1

Type RM Length L Ch R = 1 ,2422    ,482,482,482
BEGIN DESCRIPTION:
275
END DESCRIPTION:
XS GIS Cut Line= 3
        1506305.      6793637.97      1506299.62      6793332.82
      1505905.01      6792938.01
#Sta/Elev= 30
  4694.8 2324.57  4744.8 2322.83  4794.8 2318.21  4834.8 2316.56  4884.8 2312.99
  4994.8 2308.49  4997.9  2307.4  4999.9  2306.7  5006.8  2306.7  5013.7 2301.54
  5018.3 2299.18  5018.7 2298.68  5023.4 2299.18    5035  2303.2    5042 2302.94
    5162 2309.91  5259.6 2317.68  5282.4 2320.75    5317 2322.62    5402 2328.46
    5438  2331.4  5473.4 2335.94  5480.4 2337.65  5501.7 2340.53  5508.7 2342.86
  5515.8 2343.38    5537 2348.64  5544.1 2349.39  5554.7 2352.52  5558.2 2352.52
#Mann= 8 ,-1 , 0
  4694.8     .07       0  4997.9     .16       0  5018.3     .07       0
  5023.4     .16       0    5162     .07       0  5259.6     .16       0
    5317     .07       0    5402     .16       0
Bank Sta=5018.3,5023.4
XS Rating Curve= 0 ,0
Exp/Cntr=0.3,0.1

Type RM Length L Ch R = 1 ,1940    ,487,487,487
BEGIN DESCRIPTION:
274
END DESCRIPTION:
XS GIS Cut Line= 3
        1506555.      6793487.97      1506556.58      6793184.17
        1506455.        6793038.
#Sta/Elev= 30
  4696.2 2319.73  4716.2 2317.34  4826.2 2309.17  4886.2 2306.79  4916.2 2302.05
  4969.1  2300.6    4988 2300.02    5000 2299.52  5006.5 2296.26  5012.6 2298.56
  5019.7 2293.32    5031  2292.4  5031.4  2291.9  5036.1  2292.4  5042.3 2294.66
  5048.4 2292.92  5056.2 2296.85  5063.2 2301.92  5069.3 2301.34  5078.1 2307.81
  5084.2 2299.55  5092.8 2306.86    5099 2310.38  5105.1 2309.39  5113.9 2311.78
  5119.9 2311.09  5128.7 2312.19  5134.8 2311.15  5155.7 2312.28    5178 2317.19
#Mann= 5 ,-1 , 0
  4696.2     .07       0  4969.1     .16       0    4988     .07       0
    5031     .07       0  5036.1     .07       0
#XS Ineff= 2 , 0
       0    5020    2310    5045       0    2310
Permanent Ineff=
       F       F
Bank Sta=5031,5036.1
XS Rating Curve= 0 ,0
Exp/Cntr=0.3,0.1

Type RM Length L Ch R = 1 ,1453    ,455,455,455
BEGIN DESCRIPTION:
273
END DESCRIPTION:
XS GIS Cut Line= 3
        1506905.      6793388.01       1506900.8      6793036.24
      1506855.01      6792888.05
#Sta/Elev= 30
  4648.2 2312.91  4668.2  2311.3  4708.2 2309.36  4738.2 2306.86  4798.2 2304.97
  4840.1 2302.86  4878.2 2300.86  4918.2 2299.67  4928.2 2298.83  4968.2 2297.79
  4988.2  2296.5  4996.6 2293.57    5000 2293.57    5003 2290.34  5008.6 2288.54
  5016.5 2287.85  5016.9 2287.35  5021.3 2287.35  5021.7 2287.85  5029.6 2288.96
  5040.9 2291.44  5073.6 2293.61    5101 2294.22  5106.2 2294.73  5113.3 2296.23
  5123.8 2299.65  5138.8 2305.67  5144.7 2309.68  5152.5 2312.88  5155.1 2312.88
#Mann= 4 ,-1 , 0
  4648.2     .07       0  4840.1     .16       0  5016.5     .07       0
  5021.7     .16       0
Bank Sta=5016.5,5021.7
XS Rating Curve= 0 ,0
Exp/Cntr=0.3,0.1

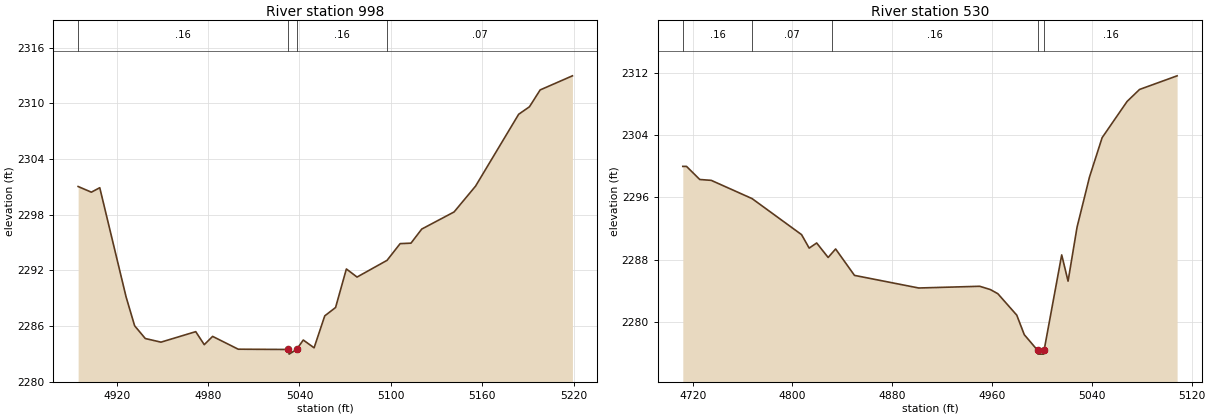
Type RM Length L Ch R = 1 ,998     ,468,468,468
BEGIN DESCRIPTION:
272
END DESCRIPTION:
XS GIS Cut Line= 3
        1507305.      6793037.99      1507260.51      6792942.56
      1507105.03      6792788.03
#Sta/Elev= 30
  4894.7 2301.04  4903.4 2300.43  4908.9 2300.91  4926.2 2289.14  4931.8 2286.04
  4938.8 2284.67  4949.1 2284.28  4971.9 2285.41  4977.5 2284.01    4983  2284.9
  4999.8 2283.52  5032.8 2283.49  5033.2 2282.99  5038.1 2283.49  5042.5 2284.51
  5049.6 2283.67  5056.6 2287.11  5063.7 2288.01  5070.8 2292.16  5077.8 2291.29
  5097.5 2293.09  5106.1 2294.89  5113.2 2294.94  5120.3 2296.46  5141.5  2298.3
  5155.6 2301.08  5183.9 2308.82    5191 2309.63    5198 2311.44  5219.2 2312.96
#Mann= 4 ,-1 , 0
  4894.7     .16       0  5032.8     .07       0  5038.1     .16       0
  5097.5     .07       0
Bank Sta=5032.8,5038.1
XS Rating Curve= 0 ,0
Exp/Cntr=0.3,0.1

Type RM Length L Ch R = 1 ,530     ,0,0,0
BEGIN DESCRIPTION:
271
END DESCRIPTION:
XS GIS Cut Line= 3
      1507454.98      6793038.02      1507611.04      6792796.08
        1507605.      6792687.95
#Sta/Elev= 30
  4712.1 2299.99  4715.1 2299.99  4725.7 2298.31  4734.9  2298.2  4767.6 2295.86
  4807.3 2291.23  4813.4  2289.5  4819.4 2290.16  4828.6  2288.3    4832 2288.92
  4834.6 2289.39  4849.7    2286  4901.2 2284.38  4950.1  2284.6  4958.6 2284.18
  4964.6 2283.65  4979.8 2280.89  4985.8 2278.39  4996.4 2276.39  4996.8 2275.89
  5001.3 2275.89  5001.7 2276.39  5015.8 2288.63  5020.9 2285.26  5028.1 2292.19
  5038.1 2298.64  5048.2 2303.68  5068.2 2308.33  5078.2 2309.87  5108.3 2311.62
#Mann= 5 ,-1 , 0
  4712.1     .16       0  4767.6     .07       0    4832     .16       0
  4996.4     .07       0  5001.7     .16       0
Bank Sta=4996.4,5001.7
XS Rating Curve= 0 ,0
Exp/Cntr=0.3,0.1

Chan Stop Cuts=-1
Use User Specified Reach Order=0
Composite Channel Slope=5