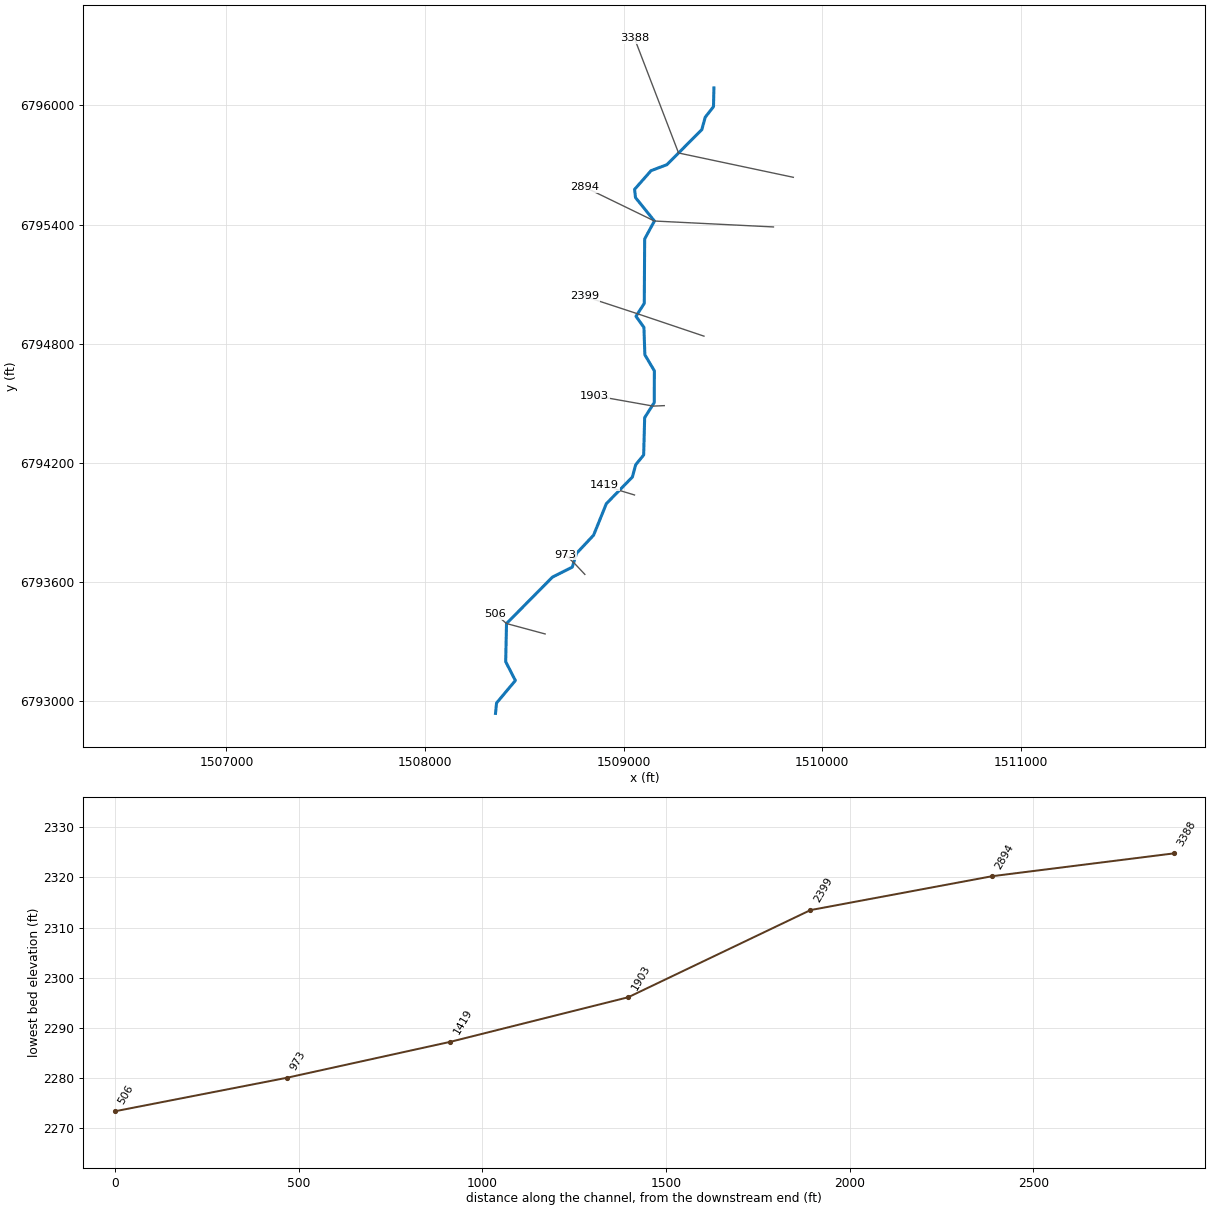
--- Elm 48.prj (project) ---

Proj Title=Elm 48 Base Level Engineering
Current Plan=p01
Default Exp/Contr=0.3,0.1
English Units
Geom File=g01
Flow File=f01
Plan File=p01
BEGIN DESCRIPTION:
Elm 48
END DESCRIPTION:

--- Elm 48.p01 (plan) ---

Plan Title=Multiple Run
Short Identifier=Multiple
Geom File=g01
Flow File=f01
Subcritical Flow
K Sum by GR= 0
Std Step Tol= 0.01
Critical Tol= 0.01
Num of Std Step Trials= 20
Max Error Tol= 0.3
Flow Tol Ratio= 0.001
Split Flow NTrial= 30
Split Flow Tol= 0.02
Split Flow Ratio= 0.02
Log Output Level= 0
Friction Slope Method= 1
Unsteady Friction Slope Method= 2
Unsteady Bridges Friction Slope Method= 1
Parabolic Critical Depth
Global Vel Dist=  1 , 1 , 1
Global Log Level= 0
CheckData=True
Encroach Param= -1, 0, 0, 0
BEGIN DESCRIPTION:
Multiple Run
END DESCRIPTION:

--- Elm 48.f01 (steady flow) ---

Flow Title=Multiple
Number of Profiles=7
Profile Names=10-year,25-year,50-year,1pct_min,100-year,1pct_plu,500-year
River Rch & RM= Elm 48,Reach-1,3388
     184     253     310     237     380     522     575
Boundary for River Rch & Prof#=Elm 48,Reach-1,1
Up Type=0
Dn Type=3
Dn Slope=0.005
Boundary for River Rch & Prof#=Elm 48,Reach-1,2
Up Type=0
Dn Type=3
Dn Slope=0.005
Boundary for River Rch & Prof#=Elm 48,Reach-1,3
Up Type=0
Dn Type=3
Dn Slope=0.005
Boundary for River Rch & Prof#=Elm 48,Reach-1,4
Up Type=0
Dn Type=3
Dn Slope=0.005
Boundary for River Rch & Prof#=Elm 48,Reach-1,5
Up Type=0
Dn Type=3
Dn Slope=0.005
Boundary for River Rch & Prof#=Elm 48,Reach-1,6
Up Type=0
Dn Type=3
Dn Slope=0.005
Boundary for River Rch & Prof#=Elm 48,Reach-1,7
Up Type=0
Dn Type=3
Dn Slope=0.005

--- Elm 48.g01 (geometry) ---

Geom Title=Existing Conditions

River Reach=Elm 48,Reach-1
Reach XY= 30
      1509455.00      6796088.00      1509452.93      6795993.86
      1509411.11      6795940.18      1509394.24      6795878.32
      1509218.21      6795701.63      1509138.29      6795671.36
      1509055.55      6795577.37      1509060.08      6795535.72
      1509155.39      6795417.87      1509106.24      6795327.50
      1509104.34      6795003.16      1509062.56      6794938.00
      1509102.53      6794882.14      1509107.27      6794743.94
      1509155.20      6794663.08      1509154.48      6794503.22
      1509106.22      6794427.49      1509101.25      6794239.55
      1509061.14      6794190.17      1509044.24      6794128.32
      1508913.14      6793994.06      1508849.15      6793835.71
      1508763.18      6793744.02      1508741.51      6793674.44
      1508641.80      6793624.36      1508410.46      6793390.45
      1508406.24      6793198.50      1508455.05      6793103.34
      1508360.33      6792990.51      1508355.00      6792938.00

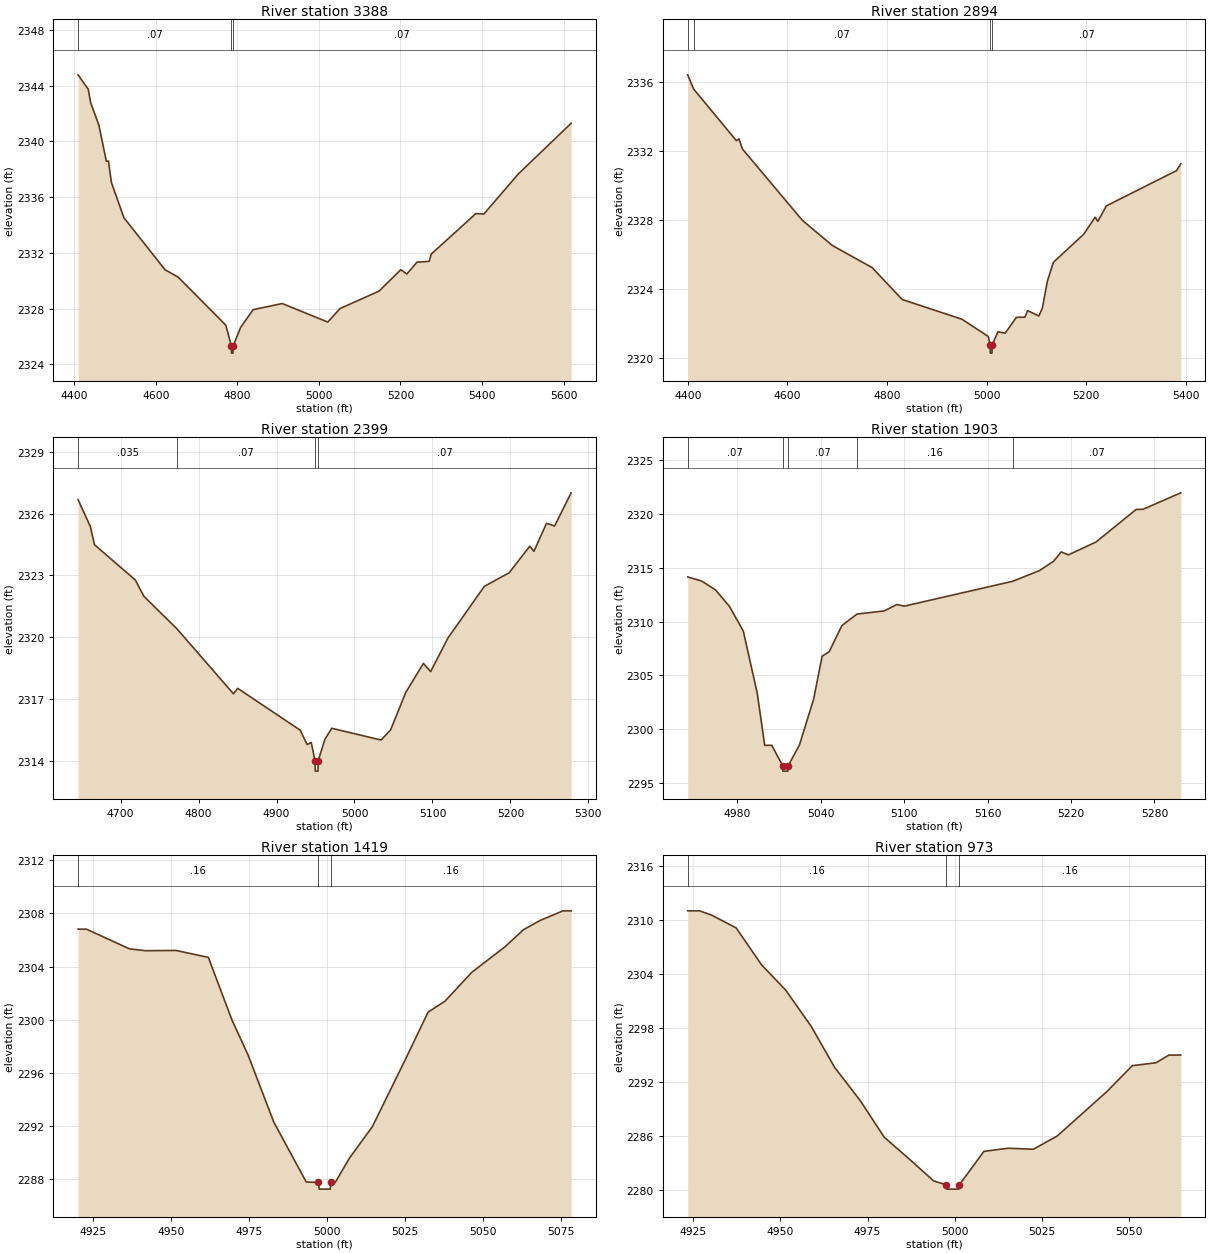
Type RM Length L Ch R = 1,3388,494,494,494
BEGIN DESCRIPTION:
430
END DESCRIPTION:
XS GIS Cut Line= 3
      1509855.04      6795637.99      1509276.89      6795760.53
      1509055.01      6796337.97
#Sta/Elev= 30
  4409.0 2344.78  4433.9 2343.75  4439.7 2342.80  4460.2 2341.15  4478.4 2338.58
  4483.6 2338.59  4490.8 2337.05  4521.5 2334.52  4622.3 2330.79  4654.4 2330.26
  4771.4 2326.81  4785.3 2325.30  4785.5 2324.80  4789.0 2324.80  4789.3 2325.30
  4807.7 2326.64  4838.4 2327.92  4909.9 2328.36  5021.6 2327.03  5051.6 2328.00
  5147.3 2329.25  5200.8 2330.79  5215.6 2330.48  5240.3 2331.33  5270.3 2331.39
  5275.8 2331.92  5385.0 2334.82  5404.3 2334.78  5488.9 2337.66  5618.6 2341.30
#Mann=3,-1,0
  4409.0    0.07       0  4785.3    0.07       0  4789.3    0.07       0
Bank Sta=4785.3,4789.3
Exp/Cntr=0.3,0.1

Type RM Length L Ch R = 1,2894,495,495,495
BEGIN DESCRIPTION:
429
END DESCRIPTION:
XS GIS Cut Line= 3
      1509754.95      6795388.00      1509155.39      6795417.87
      1508805.01      6795587.99
#Sta/Elev= 30
  4399.7 2336.44  4411.7 2335.61  4497.5 2332.61  4502.5 2332.72  4509.8 2332.12
  4629.9 2327.98  4690.0 2326.52  4770.1 2325.23  4830.2 2323.38  4950.3 2322.23
  5003.0 2321.23  5006.9 2320.76  5007.1 2320.26  5010.6 2320.26  5010.9 2320.76
  5022.7 2321.50  5037.0 2321.42  5059.6 2322.34  5076.6 2322.35  5082.1 2322.73
  5104.7 2322.42  5111.6 2322.87  5121.7 2324.44  5133.8 2325.54  5194.9 2327.18
  5217.5 2328.16  5223.1 2327.92  5240.1 2328.82  5381.0 2330.87  5389.5 2331.27
#Mann=4,-1,0
  4399.7    0.16       0  4411.7    0.07       0  5006.9    0.07       0
  5010.9    0.07       0
Bank Sta=5006.9,5010.9
Exp/Cntr=0.3,0.1

Type RM Length L Ch R = 1,2399,496,496,496
BEGIN DESCRIPTION:
428
END DESCRIPTION:
XS GIS Cut Line= 3
      1509405.00      6794838.00      1509068.95      6794951.21
      1508804.96      6795038.01
#Sta/Elev= 30
  4645.4 2326.68  4661.1 2325.38  4666.5 2324.49  4718.8 2322.78  4729.8 2321.99
  4772.2 2320.41  4844.8 2317.25  4850.1 2317.52  4930.3 2315.49  4939.3 2314.79
  4944.5 2314.89  4949.4 2314.00  4949.7 2313.50  4953.2 2313.50  4953.4 2314.00
  4962.0 2315.04  4970.8 2315.58  5034.1 2315.01  5046.3 2315.50  5065.9 2317.33
  5088.4 2318.73  5097.7 2318.33  5120.0 2319.97  5166.6 2322.47  5198.4 2323.13
  5224.9 2324.42  5230.2 2324.17  5246.3 2325.53  5256.7 2325.40  5277.9 2327.01
#Mann=4,-1,0
  4645.4   0.035       0  4772.2    0.07       0  4949.4    0.07       0
  4953.4    0.07       0
Bank Sta=4949.4,4953.4
Exp/Cntr=0.3,0.1

Type RM Length L Ch R = 1,1903,484,484,484
BEGIN DESCRIPTION:
427
END DESCRIPTION:
XS GIS Cut Line= 3
      1509205.01      6794488.00      1509149.25      6794485.67
      1508854.97      6794538.00
#Sta/Elev= 30
  4944.2 2314.13  4954.2 2313.75  4964.2 2312.93  4974.2 2311.41  4984.2 2309.11
  4994.2 2303.38  4999.6 2298.53  5004.7 2298.53  5012.5 2296.64  5012.7 2296.14
  5016.2 2296.14  5016.5 2296.64  5024.6 2298.57  5034.8 2302.81  5040.9 2306.79
  5046.0 2307.20  5055.1 2309.62  5066.0 2310.69  5085.6 2310.98  5094.8 2311.58
  5099.9 2311.42  5178.1 2313.73  5197.3 2314.72  5207.5 2315.59  5212.9 2316.45
  5218.0 2316.17  5237.9 2317.36  5266.8 2320.38  5271.9 2320.40  5298.9 2321.92
#Mann=5,-1,0
  4944.2    0.07       0  5012.5    0.07       0  5016.5    0.07       0
  5066.0    0.16       0  5178.1    0.07       0
Bank Sta=5012.5,5016.5
Exp/Cntr=0.3,0.1

Type RM Length L Ch R = 1,1419,446,446,446
BEGIN DESCRIPTION:
426
END DESCRIPTION:
XS GIS Cut Line= 3
      1509055.04      6794037.99      1508978.69      6794061.19
      1508905.01      6794087.99
#Sta/Elev= 26
  4920.2 2306.81  4922.9 2306.81  4936.7 2305.33  4941.9 2305.19  4951.6 2305.21
  4962.0 2304.69  4969.6 2299.97  4974.8 2297.32  4983.0 2292.30  4993.4 2287.80
  4997.3 2287.76  4997.6 2287.26  5001.1 2287.26  5001.3 2287.76  5002.7 2287.76
  5007.3 2289.60  5014.6 2291.95  5025.2 2297.00  5032.5 2300.57  5037.9 2301.39
  5046.5 2303.56  5057.1 2305.47  5063.1 2306.77  5068.4 2307.46  5075.8 2308.19
  5078.4 2308.19
#Mann=3,-1,0
  4920.2    0.16       0  4997.3    0.07       0  5001.3    0.16       0
Bank Sta=4997.3,5001.3
Exp/Cntr=0.3,0.1

Type RM Length L Ch R = 1,973,467,467,467
BEGIN DESCRIPTION:
425
END DESCRIPTION:
XS GIS Cut Line= 3
      1508804.97      6793638.03      1508752.54      6793693.87
      1508704.98      6793738.02
#Sta/Elev= 25
  4923.4 2311.05  4926.8 2311.05  4930.4 2310.55  4937.3 2309.15  4944.6 2305.04
  4951.5 2302.24  4958.8 2298.22  4965.6 2293.61  4972.9 2289.94  4979.8 2285.86
  4987.1 2283.39  4994.0 2280.99  4997.4 2280.58  4997.7 2280.08  5001.2 2280.08
  5001.4 2280.58  5008.4 2284.28  5015.3 2284.63  5022.6 2284.52  5029.4 2285.98
  5043.6 2290.90  5051.0 2293.82  5057.8 2294.14  5061.5 2295.00  5064.9 2295.00
#Mann=3,-1,0
  4923.4    0.16       0  4997.4    0.07       0  5001.4    0.16       0
Bank Sta=4997.4,5001.4
Exp/Cntr=0.3,0.1

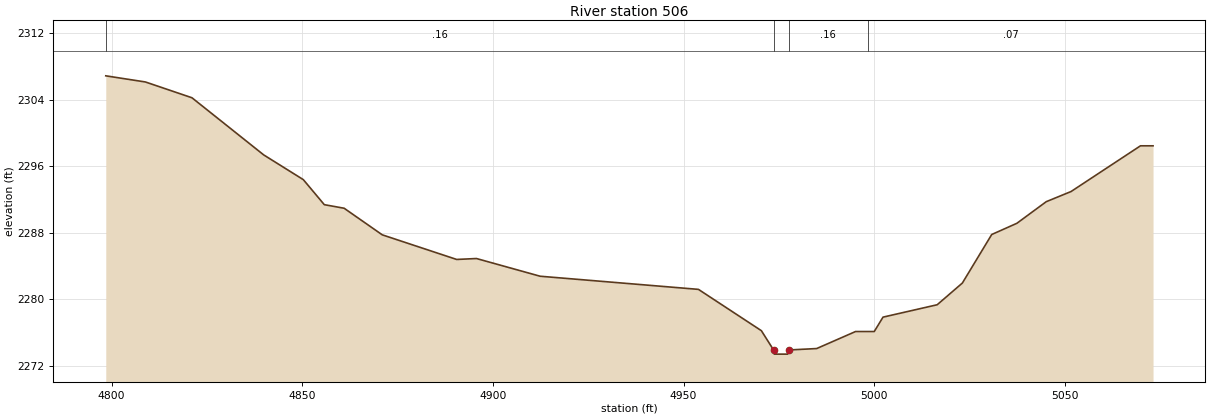
Type RM Length L Ch R = 1,506,0,0,0
BEGIN DESCRIPTION:
424
END DESCRIPTION:
XS GIS Cut Line= 3
      1508605.01      6793338.00      1508410.46      6793390.45
      1508354.96      6793438.03
#Sta/Elev= 30
  4798.5 2306.90  4808.9 2306.16  4821.1 2304.26  4839.9 2297.39  4850.3 2294.41
  4855.8 2291.40  4861.0 2290.97  4871.0 2287.77  4890.5 2284.81  4895.7 2284.92
  4912.4 2282.79  4953.9 2281.21  4970.4 2276.24  4973.6 2273.92  4973.8 2273.42
  4977.3 2273.42  4977.6 2273.92  4984.9 2274.09  4995.1 2276.14  4998.3 2276.14
  5000.0 2276.14  5002.3 2277.87  5016.5 2279.36  5023.1 2281.97  5030.8 2287.81
  5037.4 2289.16  5045.1 2291.76  5051.6 2292.98  5069.8 2298.48  5073.1 2298.48
#Mann=4,-1,0
  4798.5    0.16       0  4973.6    0.07       0  4977.6    0.16       0
  4998.3    0.07       0
Bank Sta=4973.6,4977.6
Exp/Cntr=0.3,0.1

Chan Stop Cuts=-1