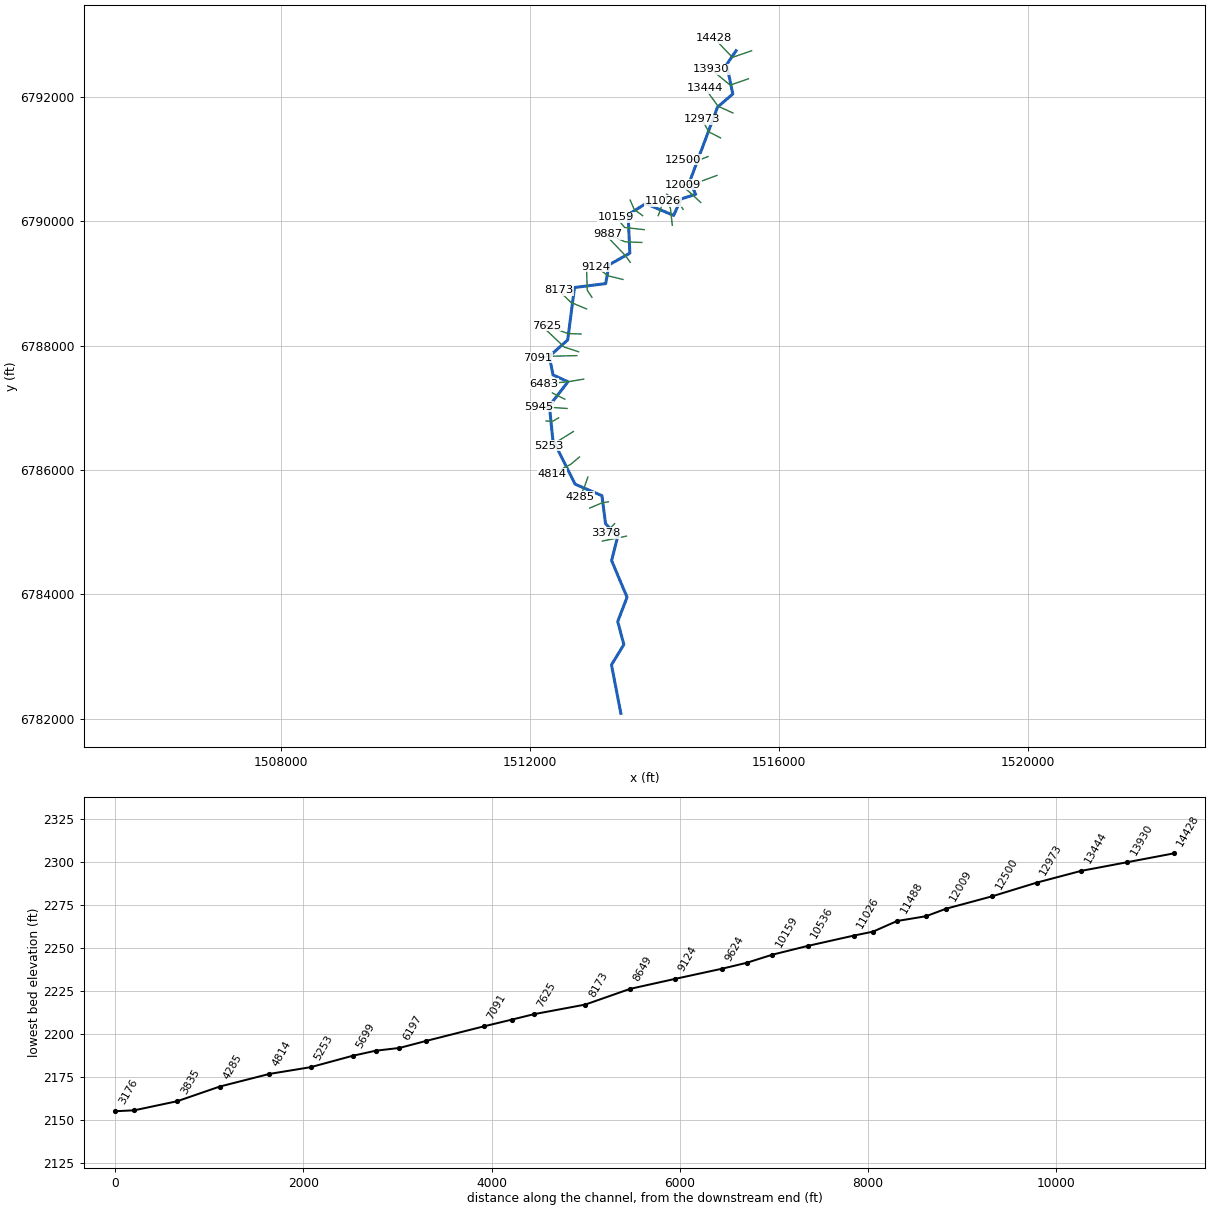
--- Elm 49.prj (project) ---

Proj Title=Elm 49 Base Level Engineering
Current Plan=p01
Default Exp/Contr=0.3,0.1
English Units
Geom File=g01
Flow File=f01
Plan File=p01
BEGIN DESCRIPTION:
Elm 49
END DESCRIPTION:

--- Elm 49.p01 (plan) ---

Plan Title=Multiple Run
Short Identifier=Multiple
Geom File=g01
Flow File=f01
Subcritical Flow
K Sum by GR= 0
Std Step Tol= 0.01
Critical Tol= 0.01
Num of Std Step Trials= 20
Max Error Tol= 0.3
Flow Tol Ratio= 0.001
Split Flow NTrial= 30
Split Flow Tol= 0.02
Split Flow Ratio= 0.02
Log Output Level= 0
Friction Slope Method= 1
Unsteady Friction Slope Method= 2
Unsteady Bridges Friction Slope Method= 1
Parabolic Critical Depth
Global Vel Dist=  1 , 1 , 1
Global Log Level= 0
CheckData=True
Encroach Param= -1, 0, 0, 0
BEGIN DESCRIPTION:
Multiple Run
END DESCRIPTION:

--- Elm 49.f01 (steady flow) ---

Flow Title=Multiple
Number of Profiles=7
Profile Names=10-year,25-year,50-year,1pct_min,100-year,1pct_plu,500-year
River Rch & RM= Elm 49,Reach-1,14428
     260     363     450     346     555     764     854
River Rch & RM= Elm 49,Reach-1,9887
     444     640     809     633    1020    1400    1620
River Rch & RM= Elm 49,Reach-1,1995
     741    1100    1410    1120    1800    2470    2960
Boundary for River Rch & Prof#=Elm 49,Reach-1,1
Up Type=0
Dn Type=3
Dn Slope=0.005
Boundary for River Rch & Prof#=Elm 49,Reach-1,2
Up Type=0
Dn Type=3
Dn Slope=0.005
Boundary for River Rch & Prof#=Elm 49,Reach-1,3
Up Type=0
Dn Type=3
Dn Slope=0.005
Boundary for River Rch & Prof#=Elm 49,Reach-1,4
Up Type=0
Dn Type=3
Dn Slope=0.005
Boundary for River Rch & Prof#=Elm 49,Reach-1,5
Up Type=0
Dn Type=3
Dn Slope=0.005
Boundary for River Rch & Prof#=Elm 49,Reach-1,6
Up Type=0
Dn Type=3
Dn Slope=0.005
Boundary for River Rch & Prof#=Elm 49,Reach-1,7
Up Type=0
Dn Type=3
Dn Slope=0.005

--- Elm 49.g01 (geometry) ---

Geom Title=Existing Conditions

River Reach=Elm 49,Reach-1
Reach XY= 30
      1515305.00      6792738.00      1515154.96      6792518.02
      1515253.11      6792043.71      1515007.32      6791832.06
      1514563.02      6790641.31      1514657.00      6790430.97
      1514421.24      6790355.22      1514303.52      6790091.45
      1513855.00      6790280.91      1513571.62      6790104.71
      1513599.66      6789485.26      1513265.47      6789297.82
      1513211.52      6788995.68      1512710.41      6788932.84
      1512601.26      6788089.56      1512305.98      6787827.73
      1512365.61      6787527.94      1512605.52      6787417.95
      1512307.00      6787032.32      1512362.78      6786484.94
      1512721.64      6785771.25      1513151.47      6785586.55
      1513208.61      6785139.50      1513403.97      6784927.55
      1513306.82      6784544.12      1513554.74      6783954.45
      1513404.71      6783565.23      1513502.94      6783193.85
      1513304.61      6782867.87      1513455.00      6782088.00

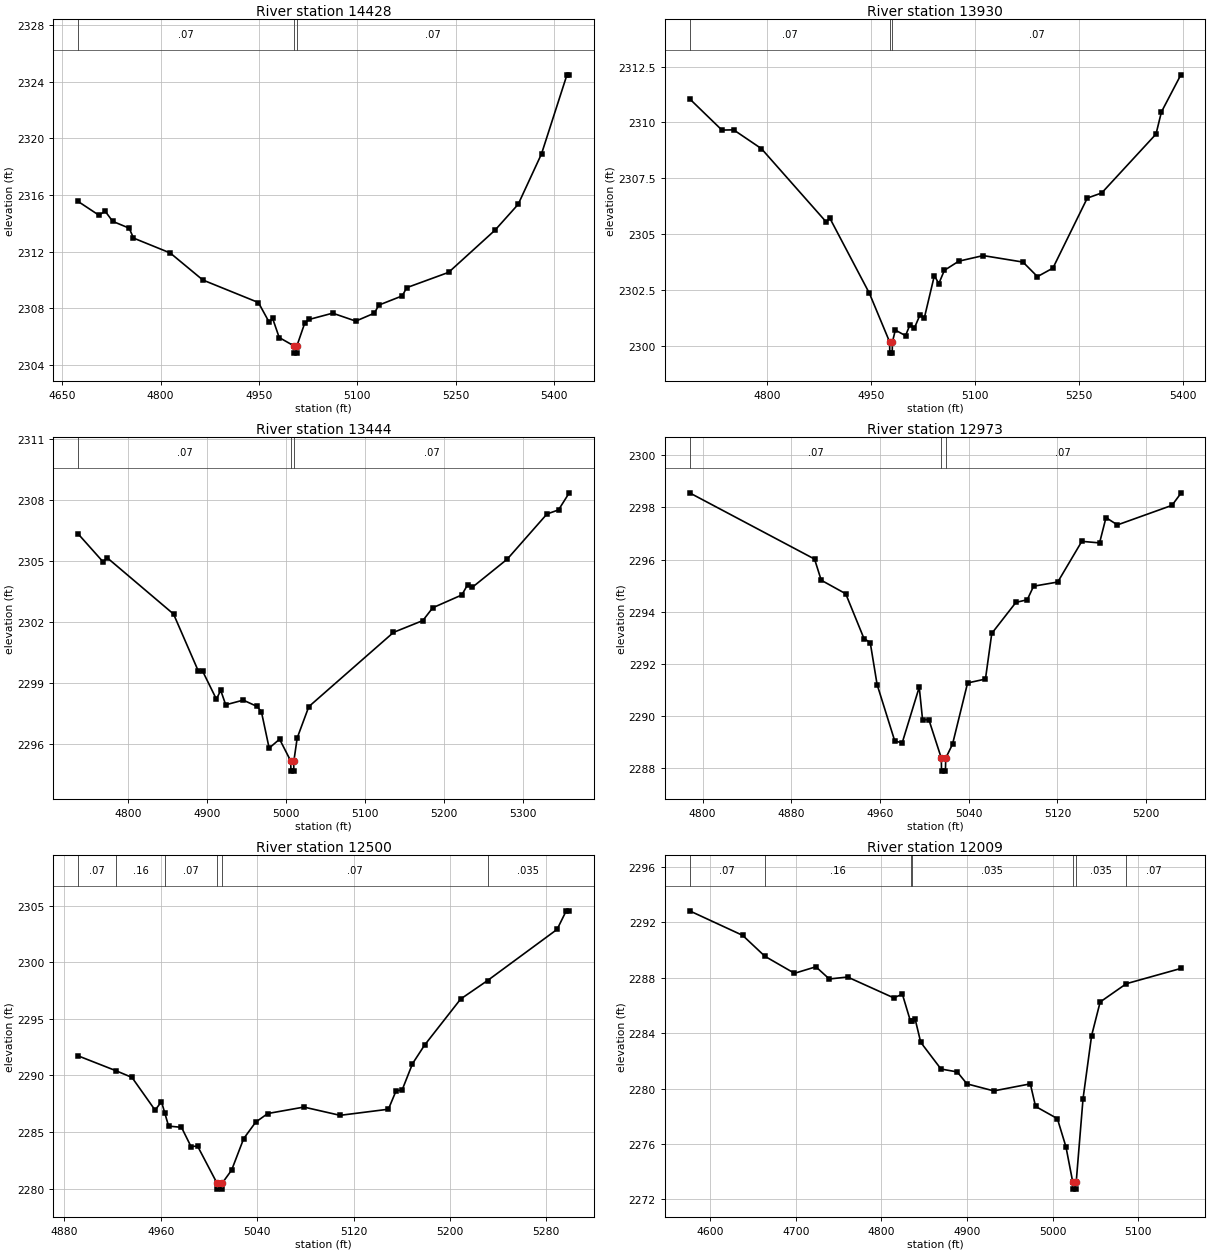
Type RM Length L Ch R = 1,14428,498,498,498
BEGIN DESCRIPTION:
127
END DESCRIPTION:
XS GIS Cut Line= 3
      1515554.97      6792737.99      1515246.93      6792631.92
      1514954.98      6792938.02
#Sta/Elev= 30
  4674.2 2315.55  4705.9 2314.58  4715.7 2314.85  4727.1 2314.14  4752.2 2313.66
  4758.8 2312.96  4814.7 2311.91  4864.5 2310.00  4949.2 2308.41  4965.5 2307.03
  4970.8 2307.30  4980.9 2305.94  5003.8 2305.34  5004.0 2304.84  5007.5 2304.84
  5007.8 2305.34  5019.9 2306.97  5026.8 2307.22  5062.4 2307.66  5097.6 2307.10
  5125.9 2307.66  5132.8 2308.23  5168.4 2308.88  5175.3 2309.46  5239.1 2310.54
  5309.9 2313.52  5345.1 2315.34  5380.7 2318.90  5419.5 2324.48  5423.0 2324.48
#Mann=3,-1,0
  4674.2    0.07       0  5003.8    0.07       0  5007.8    0.07       0
Bank Sta=5003.8,5007.8
Exp/Cntr=0.3,0.1

Type RM Length L Ch R = 1,13930,486,486,486
BEGIN DESCRIPTION:
126
END DESCRIPTION:
XS GIS Cut Line= 3
      1515504.97      6792287.99      1515211.12      6792185.82
      1514905.01      6792437.99
#Sta/Elev= 30
  4688.9 2311.06  4735.5 2309.66  4752.4 2309.67  4792.4 2308.83  4885.8 2305.55
  4891.0 2305.72  4948.0 2302.36  4977.1 2300.19  4977.3 2299.69  4980.8 2299.69
  4981.1 2300.19  4985.3 2300.72  5000.0 2300.47  5006.4 2300.96  5012.9 2300.82
  5020.7 2301.39  5027.2 2301.28  5041.5 2303.15  5048.0 2302.80  5055.9 2303.39
  5076.7 2303.80  5111.9 2304.05  5169.2 2303.76  5190.0 2303.11  5212.3 2303.49
  5261.8 2306.62  5282.6 2306.85  5360.8 2309.48  5368.6 2310.47  5396.6 2312.13
#Mann=3,-1,0
  4688.9    0.07       0  4977.1    0.07       0  4981.1    0.07       0
Bank Sta=4977.1,4981.1
Exp/Cntr=0.3,0.1

Type RM Length L Ch R = 1,13444,471,471,471
BEGIN DESCRIPTION:
125
END DESCRIPTION:
XS GIS Cut Line= 3
      1515254.96      6791738.02      1515015.81      6791847.71
      1514804.98      6792138.03
#Sta/Elev= 30
  4736.9 2306.36  4768.6 2304.98  4774.1 2305.17  4857.9 2302.41  4889.1 2299.62
  4894.6 2299.61  4912.1 2298.23  4917.6 2298.66  4923.9 2297.95  4946.1 2298.18
  4963.6 2297.87  4969.1 2297.61  4978.9 2295.82  4992.1 2296.26  5006.2 2295.19
  5006.5 2294.69  5010.0 2294.69  5010.2 2295.19  5014.4 2296.32  5029.1 2297.86
  5136.3 2301.51  5173.4 2302.09  5186.0 2302.72  5222.8 2303.35  5230.1 2303.85
  5236.2 2303.73  5280.3 2305.11  5330.6 2307.33  5345.2 2307.53  5358.8 2308.37
#Mann=3,-1,0
  4736.9    0.07       0  5006.2    0.07       0  5010.2    0.07       0
Bank Sta=5006.2,5010.2
Exp/Cntr=0.3,0.1

Type RM Length L Ch R = 1,12973,473,473,473
BEGIN DESCRIPTION:
124
END DESCRIPTION:
XS GIS Cut Line= 3
      1515055.00      6791338.00      1514867.24      6791435.79
      1514754.99      6791638.03
#Sta/Elev= 30
  4788.3 2298.56  4901.0 2296.02  4907.0 2295.21  4929.1 2294.69  4945.6 2292.97
  4951.2 2292.82  4957.4 2291.21  4973.3 2289.05  4980.0 2288.97  4995.4 2291.11
  4998.4 2289.86  5004.1 2289.86  5015.3 2288.39  5015.5 2287.89  5019.0 2287.89
  5019.3 2288.39  5025.4 2288.92  5039.0 2291.27  5055.1 2291.42  5060.8 2293.17
  5082.6 2294.36  5092.8 2294.46  5098.5 2294.98  5120.3 2295.14  5142.0 2296.70
  5158.0 2296.64  5163.8 2297.61  5174.1 2297.33  5223.3 2298.08  5231.3 2298.54
#Mann=3,-1,0
  4788.3    0.07       0  5015.3    0.07       0  5019.3    0.07       0
Bank Sta=5015.3,5019.3
Exp/Cntr=0.3,0.1

Type RM Length L Ch R = 1,12500,491,491,491
BEGIN DESCRIPTION:
123
END DESCRIPTION:
XS GIS Cut Line= 3
      1514855.04      6791038.01      1514753.77      6790998.51
      1514454.96      6790988.00
#Sta/Elev= 30
  4891.3 2291.74  4923.1 2290.41  4936.1 2289.83  4955.3 2286.94  4960.6 2287.69
  4963.4 2286.66  4966.5 2285.53  4977.2 2285.42  4985.1 2283.72  4990.5 2283.77
  5006.8 2280.46  5007.0 2279.96  5010.5 2279.96  5010.8 2280.46  5018.8 2281.64
  5028.8 2284.42  5038.8 2285.88  5048.8 2286.64  5078.8 2287.21  5108.8 2286.48
  5148.9 2287.02  5155.3 2288.65  5160.3 2288.72  5168.9 2291.04  5178.9 2292.68
  5208.9 2296.76  5231.2 2298.39  5288.9 2302.91  5296.5 2304.55  5299.0 2304.55
#Mann=6,-1,0
  4891.3    0.07       0  4923.1    0.16       0  4963.4    0.07       0
  5006.8    0.07       0  5010.8    0.07       0  5231.2   0.035       0
Bank Sta=5006.8,5010.8
Exp/Cntr=0.3,0.1

Type RM Length L Ch R = 1,12009,214,214,214
BEGIN DESCRIPTION:
122
END DESCRIPTION:
XS GIS Cut Line= 3
      1514998.01      6790734.72      1514600.61      6790586.35
      1514450.73      6790584.08
#Sta/Elev= 30
  4575.8 2292.83  4637.8 2291.06  4663.8 2289.55  4698.4 2288.32  4723.4 2288.79
  4739.1 2287.91  4760.5 2288.05  4814.3 2286.55  4824.5 2286.81  4834.0 2284.85
  4835.3 2284.90  4839.3 2285.04  4845.9 2283.34  4869.6 2281.41  4888.6 2281.20
  4899.9 2280.34  4931.3 2279.83  4974.0 2280.34  4980.1 2278.71  5005.6 2277.83
  5015.6 2275.80  5023.6 2273.24  5023.9 2272.74  5027.4 2272.74  5027.6 2273.24
  5035.6 2279.27  5045.6 2283.82  5055.6 2286.25  5086.2 2287.57  5149.9 2288.67
#Mann=7,-1,0
  4575.8    0.07       0  4663.8    0.16       0  4834.0    0.07       0
  4835.3   0.035       0  5023.6   0.035       0  5027.6   0.035       0
  5086.2    0.07       0
Bank Sta=5023.6,5027.6
Exp/Cntr=0.3,0.1

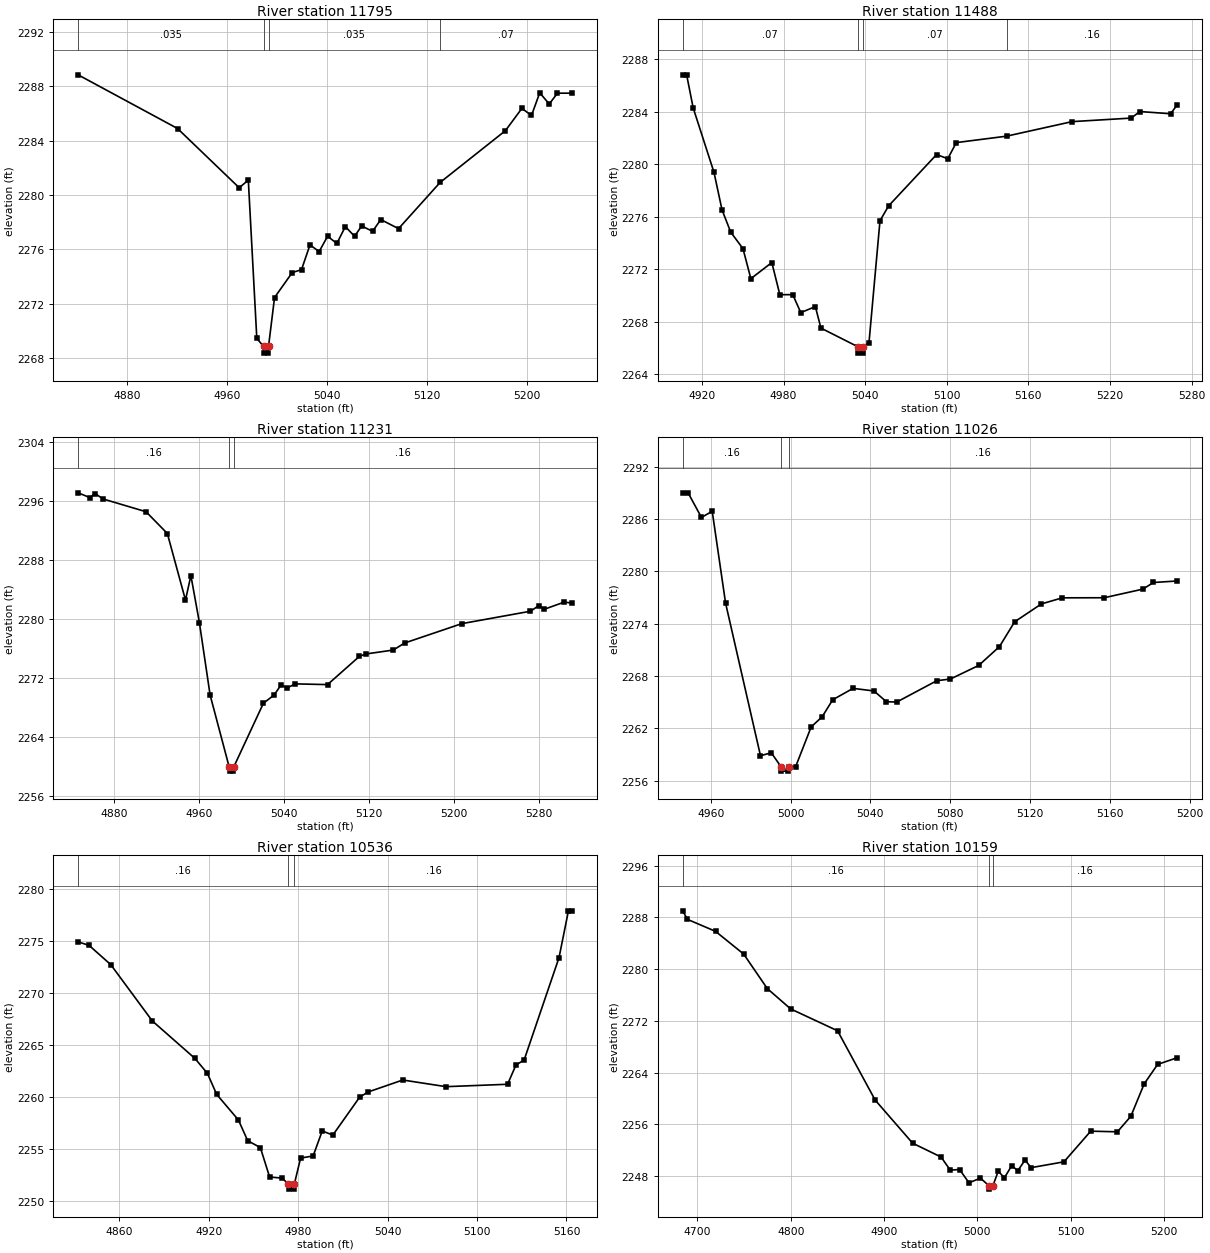
Type RM Length L Ch R = 1,11795,307,307,307
BEGIN DESCRIPTION:
852
END DESCRIPTION:
XS GIS Cut Line= 3
      1514738.85      6790299.28      1514571.57      6790454.11
      1514444.29      6790563.71
#Sta/Elev= 30
  4840.6 2288.85  4920.2 2284.90  4969.6 2280.54  4976.9 2281.10  4983.7 2269.45
  4989.1 2268.87  4989.4 2268.37  4992.9 2268.37  4993.1 2268.87  4997.9 2272.46
  5012.1 2274.30  5019.5 2274.51  5026.3 2276.34  5033.6 2275.84  5040.4 2276.97
  5047.8 2276.44  5054.6 2277.68  5062.0 2276.97  5067.7 2277.73  5076.4 2277.33
  5083.0 2278.20  5097.2 2277.53  5130.5 2280.93  5182.8 2284.74  5196.0 2286.38
  5203.7 2285.86  5210.3 2287.53  5217.9 2286.70  5224.5 2287.50  5236.5 2287.50
#Mann=4,-1,0
  4840.6   0.035       0  4989.1   0.035       0  4993.1   0.035       0
  5130.5    0.07       0
Bank Sta=4989.1,4993.1
Exp/Cntr=0.3,0.1

Type RM Length L Ch R = 1,11488,257,257,257
BEGIN DESCRIPTION:
121
END DESCRIPTION:
XS GIS Cut Line= 3
      1514454.99      6790188.02      1514405.31      6790267.93
      1514192.81      6790433.21
#Sta/Elev= 30
  4905.9 2286.83  4908.8 2286.83  4913.6 2284.31  4928.9 2279.39  4934.8 2276.53
  4941.2 2274.83  4950.2 2273.57  4956.0 2271.28  4971.4 2272.51  4977.3 2270.06
  4986.8 2270.06  4992.7 2268.69  5003.4 2269.15  5007.5 2267.51  5034.4 2266.10
  5034.7 2265.60  5038.2 2265.60  5038.4 2266.10  5042.8 2266.38  5050.9 2275.70
  5057.3 2276.84  5092.5 2280.75  5100.7 2280.43  5107.0 2281.66  5143.9 2282.15
  5192.1 2283.26  5235.5 2283.53  5241.9 2284.03  5264.5 2283.86  5269.2 2284.52
#Mann=4,-1,0
  4905.9    0.07       0  5034.4    0.07       0  5038.4    0.07       0
  5143.9    0.16       0
Bank Sta=5034.4,5038.4
Exp/Cntr=0.3,0.1

Type RM Length L Ch R = 1,11231,205,205,205
BEGIN DESCRIPTION:
850
END DESCRIPTION:
XS GIS Cut Line= 3
      1514281.48      6789934.40      1514251.22      6790204.94
      1514178.95      6790384.73
#Sta/Elev= 30
  4845.8 2297.11  4856.8 2296.47  4861.8 2297.00  4869.5 2296.27  4909.8 2294.55
  4929.9 2291.60  4947.0 2282.58  4952.1 2285.90  4960.1 2279.54  4970.2 2269.73
  4988.3 2259.91  4988.5 2259.41  4992.0 2259.41  4992.3 2259.91  5020.5 2268.62
  5030.5 2269.71  5037.3 2271.13  5042.3 2270.66  5050.7 2271.23  5080.9 2271.13
  5111.0 2274.96  5117.0 2275.28  5142.8 2275.81  5153.7 2276.77  5207.5 2279.39
  5272.2 2281.07  5279.9 2281.81  5285.3 2281.34  5304.1 2282.31  5311.8 2282.16
#Mann=3,-1,0
  4845.8    0.16       0  4988.3    0.07       0  4992.3    0.16       0
Bank Sta=4988.3,4992.3
Exp/Cntr=0.3,0.1

Type RM Length L Ch R = 1,11026,490,490,490
BEGIN DESCRIPTION:
120
END DESCRIPTION:
XS GIS Cut Line= 3
      1514055.00      6790088.00      1514075.09      6790138.23
      1514134.10      6790322.72
#Sta/Elev= 30
  4945.9 2289.02  4948.6 2289.02  4955.3 2286.20  4960.7 2286.90  4967.4 2276.37
  4984.9 2258.87  4990.3 2259.22  4995.2 2257.61  4995.4 2257.11  4998.9 2257.11
  4999.2 2257.61  5002.5 2257.61  5010.3 2262.18  5015.8 2263.34  5021.1 2265.29
  5031.3 2266.60  5041.8 2266.30  5048.0 2265.07  5053.2 2265.03  5073.3 2267.48
  5080.1 2267.67  5094.3 2269.23  5104.7 2271.39  5112.3 2274.23  5125.7 2276.28
  5136.2 2276.98  5157.2 2276.99  5176.6 2277.98  5181.9 2278.74  5193.7 2278.91
#Mann=3,-1,0
  4945.9    0.16       0  4995.2    0.07       0  4999.2    0.16       0
Bank Sta=4995.2,4999.2
Exp/Cntr=0.3,0.1

Type RM Length L Ch R = 1,10536,377,377,377
BEGIN DESCRIPTION:
119
END DESCRIPTION:
XS GIS Cut Line= 3
      1513804.98      6790088.01      1513670.21      6790187.48
      1513605.02      6790337.96
#Sta/Elev= 30
  4832.5 2274.90  4839.8 2274.57  4854.4 2272.71  4882.2 2267.30  4910.8 2263.69
  4919.2 2262.25  4925.4 2260.23  4940.0 2257.76  4946.2 2255.77  4954.7 2255.11
  4960.9 2252.28  4969.2 2252.17  4973.5 2251.61  4973.8 2251.11  4977.3 2251.11
  4977.5 2251.61  4981.7 2254.10  4990.1 2254.30  4996.2 2256.71  5003.3 2256.31
  5021.3 2259.96  5026.8 2260.45  5050.2 2261.61  5079.2 2260.97  5120.5 2261.20
  5126.1 2263.05  5131.6 2263.54  5155.0 2273.39  5161.3 2277.89  5164.0 2277.89
#Mann=3,-1,0
  4832.5    0.16       0  4973.5    0.07       0  4977.5    0.16       0
Bank Sta=4973.5,4977.5
Exp/Cntr=0.3,0.1

Type RM Length L Ch R = 1,10159,272,272,272
BEGIN DESCRIPTION:
118
END DESCRIPTION:
XS GIS Cut Line= 3
      1513830.02      6789863.00      1513516.14      6789897.79
      1513379.99      6790063.01
#Sta/Elev= 30
  4684.2 2289.02  4689.3 2287.70  4719.4 2285.85  4749.6 2282.33  4774.9 2277.00
  4799.9 2273.86  4850.2 2270.48  4890.5 2259.77  4930.7 2253.10  4961.2 2250.96
  4971.0 2248.94  4981.0 2249.03  4991.1 2246.98  5003.4 2247.70  5012.7 2246.50
  5012.9 2246.00  5016.7 2246.50  5022.5 2248.79  5029.0 2247.73  5036.9 2249.63
  5043.4 2248.85  5051.2 2250.49  5057.7 2249.32  5092.9 2250.22  5121.6 2254.96
  5150.2 2254.86  5164.6 2257.26  5178.9 2262.27  5193.3 2265.28  5214.1 2266.30
#Mann=3,-1,0
  4684.2    0.16       0  5012.7    0.07       0  5016.7    0.16       0
Bank Sta=5012.7,5016.7
Exp/Cntr=0.3,0.1

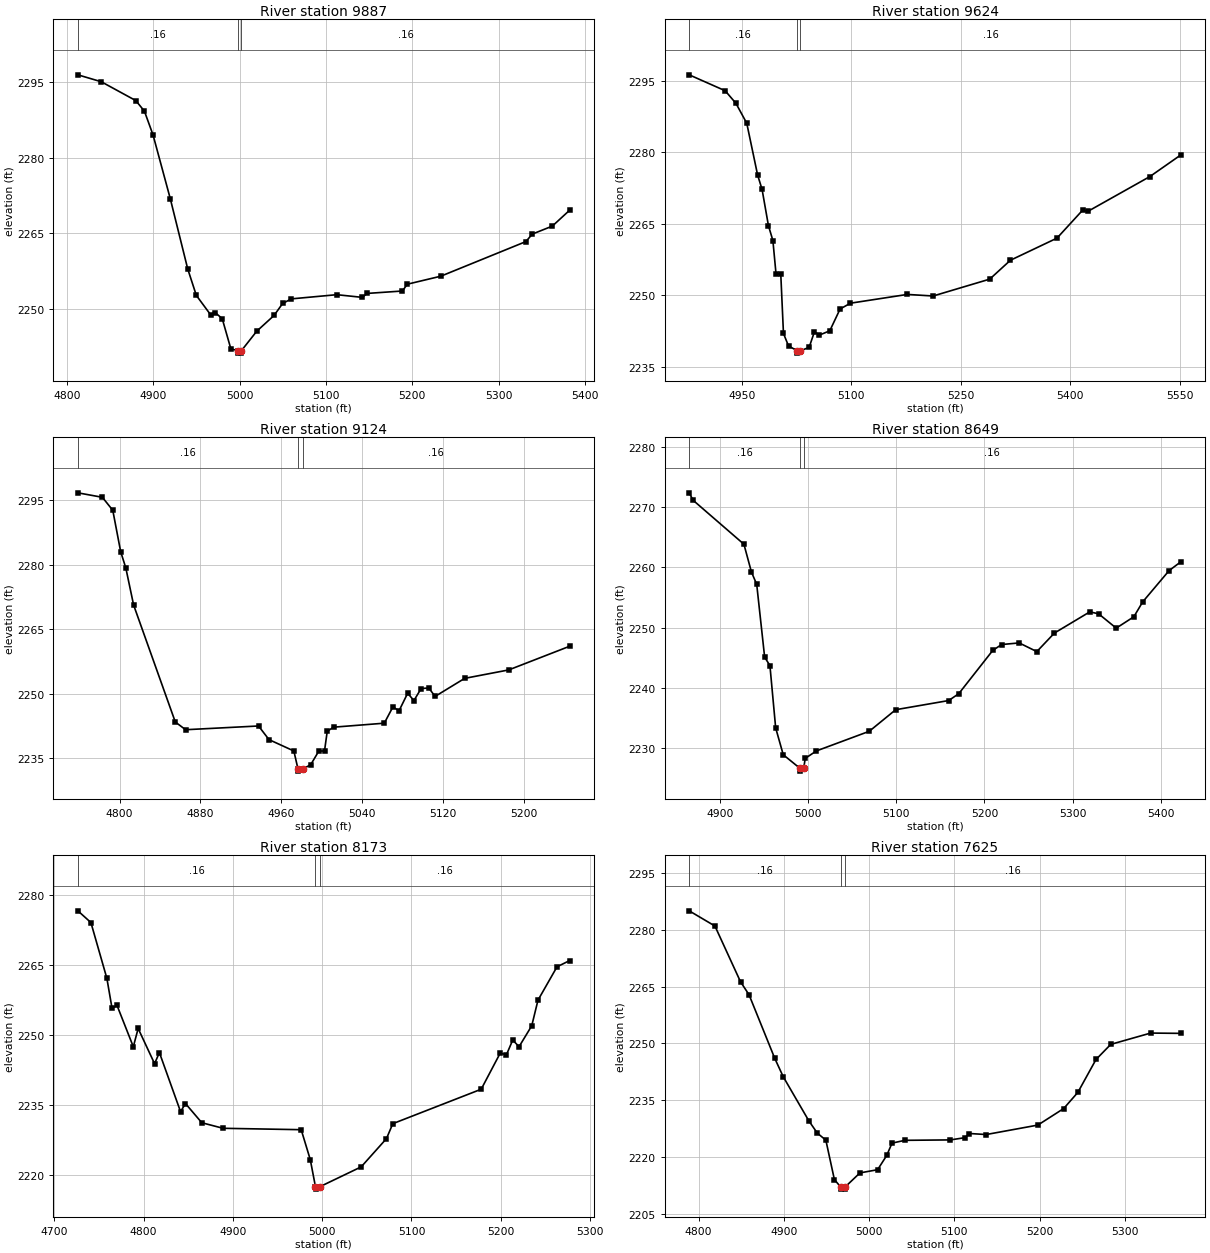
Type RM Length L Ch R = 1,9887,263,263,263
BEGIN DESCRIPTION:
851
END DESCRIPTION:
XS GIS Cut Line= 3
      1513792.05      6789656.78      1513523.31      6789667.46
      1513248.74      6789789.69
#Sta/Elev= 30
  4812.6 2296.40  4839.7 2295.03  4879.7 2291.30  4889.7 2289.20  4899.7 2284.48
  4919.7 2271.84  4939.8 2258.00  4949.8 2252.73  4967.0 2248.75  4972.0 2249.28
  4979.8 2248.13  4989.8 2242.15  4997.6 2241.80  4997.9 2241.30  5001.7 2241.30
  5002.1 2241.80  5019.8 2245.64  5039.8 2248.75  5049.8 2251.13  5059.8 2252.04
  5112.5 2252.87  5142.1 2252.34  5147.6 2253.12  5188.6 2253.60  5194.1 2254.94
  5233.0 2256.53  5331.5 2263.38  5339.0 2264.87  5362.2 2266.45  5382.1 2269.57
#Mann=3,-1,0
  4812.6    0.16       0  4997.6    0.07       0  5002.1    0.16       0
Bank Sta=4997.6,5002.1
Exp/Cntr=0.3,0.1

Type RM Length L Ch R = 1,9624,500,500,500
BEGIN DESCRIPTION:
117
END DESCRIPTION:
XS GIS Cut Line= 3
      1513605.00      6789337.99      1513535.06      6789438.08
      1513155.01      6789837.99
#Sta/Elev= 30
  4877.9 2296.28  4927.2 2292.94  4942.0 2290.29  4956.8 2286.11  4971.7 2275.23
  4977.8 2272.22  4986.5 2264.63  4992.6 2261.50  4996.9 2254.50  5003.4 2254.50
  5007.1 2242.00  5014.0 2239.39  5025.9 2238.37  5026.2 2237.87  5030.4 2238.37
  5042.3 2239.08  5049.5 2242.34  5056.4 2241.66  5070.6 2242.56  5084.7 2247.13
  5098.9 2248.35  5176.9 2250.19  5212.2 2249.86  5289.8 2253.40  5318.1 2257.36
  5382.0 2262.01  5417.2 2267.89  5424.5 2267.64  5509.4 2274.94  5551.7 2279.47
#Mann=3,-1,0
  4877.9    0.16       0  5025.9    0.07       0  5030.4    0.16       0
Bank Sta=5025.9,5030.4
Exp/Cntr=0.3,0.1

Type RM Length L Ch R = 1,9124,475,475,475
BEGIN DESCRIPTION:
116
END DESCRIPTION:
XS GIS Cut Line= 3
      1513488.46      6789062.25      1513254.25      6789119.88
      1513056.44      6789264.10
#Sta/Elev= 30
  4758.8 2296.74  4783.0 2295.70  4793.3 2292.68  4801.1 2283.05  4806.2 2279.24
  4813.9 2270.62  4855.1 2243.39  4865.3 2241.59  4937.4 2242.46  4947.7 2239.29
  4972.3 2236.64  4976.4 2232.45  4976.7 2231.95  4980.9 2232.45  4988.9 2233.42
  4997.0 2236.63  5002.6 2236.63  5005.3 2241.22  5011.5 2242.18  5061.7 2243.11
  5070.2 2246.89  5076.3 2246.01  5084.8 2250.08  5091.0 2248.38  5098.1 2251.17
  5105.7 2251.31  5111.9 2249.34  5141.2 2253.55  5184.7 2255.51  5244.8 2261.01
#Mann=3,-1,0
  4758.8    0.16       0  4976.4    0.07       0  4980.9    0.16       0
Bank Sta=4976.4,4980.9
Exp/Cntr=0.3,0.1

Type RM Length L Ch R = 1,8649,476,476,476
BEGIN DESCRIPTION:
115
END DESCRIPTION:
XS GIS Cut Line= 3
      1512990.45      6788776.30      1512915.71      6788888.72
      1512901.27      6789311.27
#Sta/Elev= 30
  4865.0 2272.37  4869.4 2271.14  4927.1 2263.84  4935.6 2259.24  4941.6 2257.19
  4950.6 2245.11  4956.6 2243.71  4963.1 2233.38  4971.7 2228.92  4990.4 2226.70
  4990.7 2226.20  4995.0 2226.70  4996.6 2228.31  5009.3 2229.55  5069.3 2232.81
  5099.3 2236.39  5159.4 2237.91  5170.8 2239.04  5209.4 2246.22  5219.4 2247.20
  5239.4 2247.47  5259.4 2246.03  5279.4 2249.11  5319.5 2252.62  5329.5 2252.30
  5349.5 2249.92  5369.5 2251.81  5379.5 2254.27  5409.5 2259.47  5422.8 2260.93
#Mann=3,-1,0
  4865.0    0.16       0  4990.4    0.07       0  4995.0    0.16       0
Bank Sta=4990.4,4995
Exp/Cntr=0.3,0.1

Type RM Length L Ch R = 1,8173,548,548,548
BEGIN DESCRIPTION:
114
END DESCRIPTION:
XS GIS Cut Line= 3
      1512904.99      6788588.01      1512652.73      6788693.94
      1512455.03      6788887.97
#Sta/Elev= 30
  4726.4 2276.69  4741.0 2274.18  4758.9 2262.21  4764.7 2255.77  4770.2 2256.45
  4788.5 2247.57  4793.9 2251.49  4812.3 2243.95  4817.7 2246.33  4841.4 2233.67
  4846.9 2235.41  4865.2 2231.30  4889.0 2230.11  4976.5 2229.81  4986.7 2223.38
  4992.5 2217.58  4992.8 2217.08  4997.2 2217.58  5043.7 2221.85  5072.0 2227.90
  5079.1 2231.10  5178.1 2238.48  5199.3 2246.18  5206.4 2245.88  5213.4 2249.01
  5220.5 2247.59  5234.7 2252.07  5241.7 2257.56  5263.0 2264.70  5277.0 2266.02
#Mann=3,-1,0
  4726.4    0.16       0  4992.5    0.07       0  4997.2    0.16       0
Bank Sta=4992.5,4997.2
Exp/Cntr=0.3,0.1

Type RM Length L Ch R = 1,7625,233,233,233
BEGIN DESCRIPTION:
113
END DESCRIPTION:
XS GIS Cut Line= 3
      1512815.20      6788186.04      1512605.31      6788192.96
      1512261.81      6788321.31
#Sta/Elev= 30
  4788.9 2285.04  4819.1 2281.02  4849.1 2266.29  4859.1 2262.86  4889.2 2246.08
  4899.2 2241.19  4929.2 2229.55  4939.2 2226.28  4949.2 2224.43  4959.2 2214.02
  4966.8 2211.98  4967.2 2211.48  4971.2 2211.48  4971.5 2211.98  4989.2 2215.77
  5009.9 2216.61  5020.6 2220.38  5026.8 2223.64  5041.9 2224.38  5095.3 2224.49
  5112.3 2225.08  5117.7 2226.18  5137.3 2225.91  5197.9 2228.41  5228.2 2232.78
  5244.8 2237.05  5266.1 2245.75  5283.4 2249.74  5330.2 2252.73  5365.6 2252.65
#Mann=3,-1,0
  4788.9    0.16       0  4966.8    0.07       0  4971.5    0.16       0
Bank Sta=4966.8,4971.5
Exp/Cntr=0.3,0.1

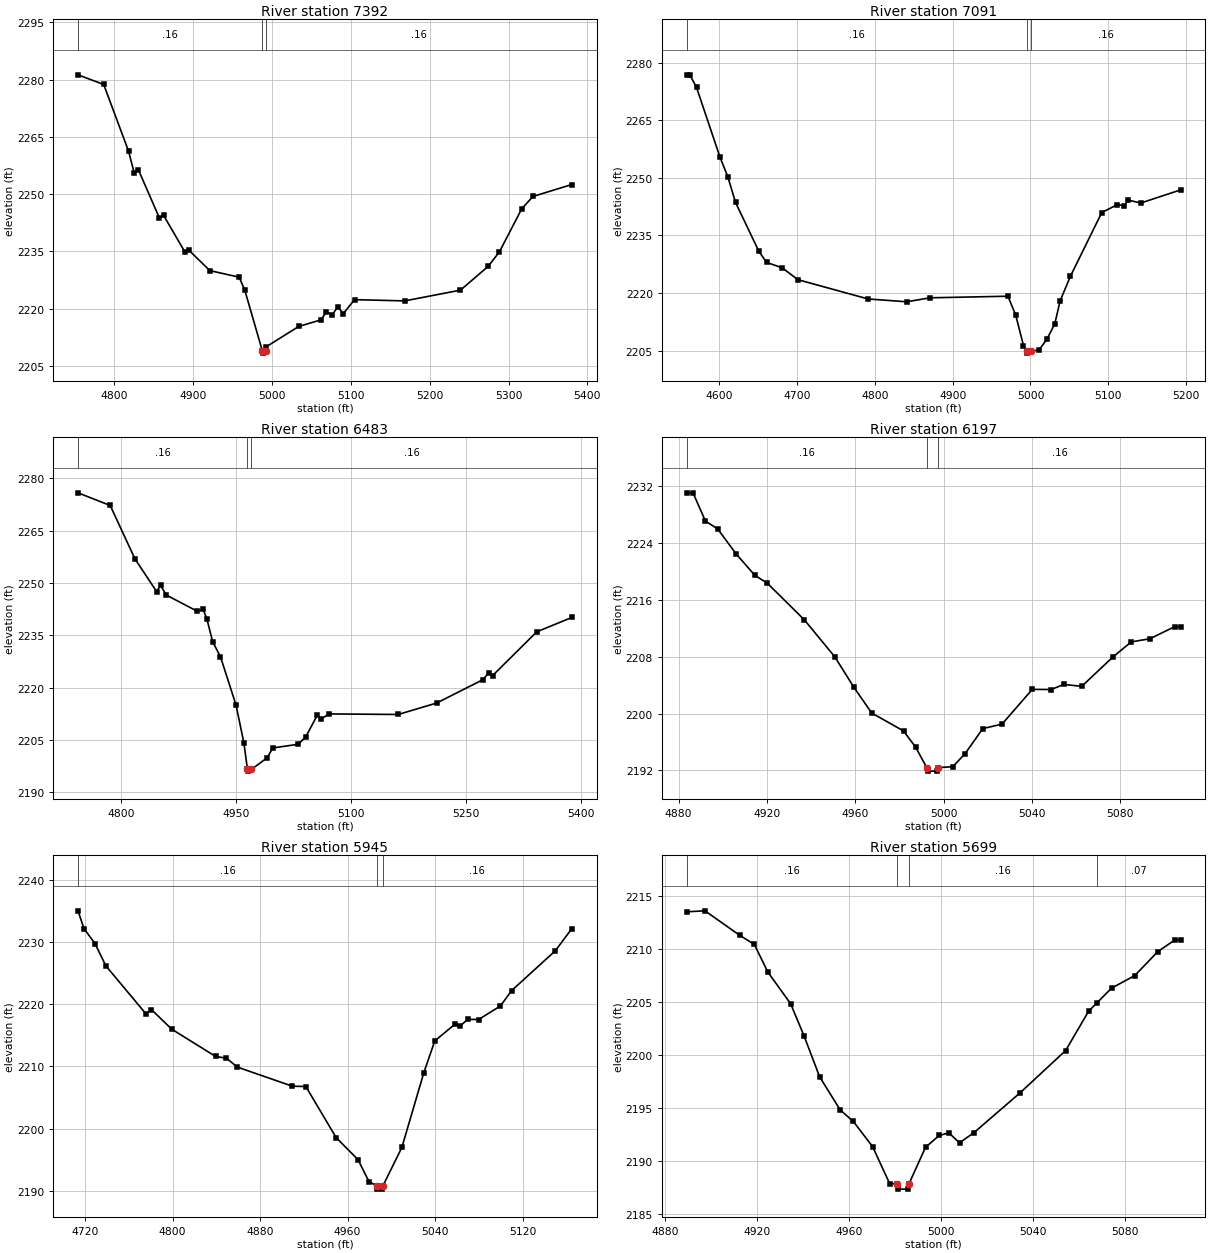
Type RM Length L Ch R = 1,7392,301,301,301
BEGIN DESCRIPTION:
849
END DESCRIPTION:
XS GIS Cut Line= 3
      1512775.99      6787900.34      1512548.03      6787974.56
      1512267.07      6788239.62
#Sta/Elev= 30
  4754.3 2281.24  4786.9 2278.71  4818.4 2261.25  4825.6 2255.50  4830.9 2256.35
  4857.5 2243.73  4862.8 2244.43  4889.5 2234.94  4894.7 2235.33  4921.4 2229.96
  4958.6 2228.23  4965.7 2224.85  4988.1 2208.84  4988.5 2208.34  4992.8 2208.84
  4993.0 2210.02  5034.0 2215.32  5062.4 2217.06  5069.2 2219.21  5076.5 2218.31
  5083.4 2220.45  5090.7 2218.71  5104.8 2222.35  5168.3 2222.02  5239.1 2224.84
  5274.3 2231.09  5288.5 2234.89  5316.8 2246.17  5331.0 2249.38  5380.3 2252.51
#Mann=3,-1,0
  4754.3    0.16       0  4988.1    0.07       0  4992.8    0.16       0
Bank Sta=4988.1,4992.8
Exp/Cntr=0.3,0.1

Type RM Length L Ch R = 1,7091,608,608,608
BEGIN DESCRIPTION:
112
END DESCRIPTION:
XS GIS Cut Line= 3
      1512747.54      6787838.64      1512305.98      6787827.73
      1512114.24      6787804.82
#Sta/Elev= 30
  4558.3 2276.80  4562.1 2276.80  4570.8 2273.51  4600.9 2255.38  4610.9 2250.34
  4620.9 2243.60  4650.9 2230.88  4660.9 2227.98  4680.9 2226.59  4700.9 2223.51
  4791.3 2218.48  4840.9 2217.75  4870.9 2218.78  4971.0 2219.20  4981.0 2214.29
  4991.0 2206.37  4995.4 2204.89  4995.8 2204.39  5000.6 2204.89  5011.1 2205.25
  5021.1 2208.00  5031.2 2212.00  5038.1 2217.98  5051.3 2224.38  5091.6 2240.96
  5111.8 2243.05  5120.5 2242.70  5125.5 2244.19  5142.0 2243.46  5193.1 2246.87
#Mann=3,-1,0
  4558.3    0.16       0  4995.4    0.07       0  5000.6    0.16       0
Bank Sta=4995.4,5000.6
Exp/Cntr=0.3,0.1

Type RM Length L Ch R = 1,6483,286,286,286
BEGIN DESCRIPTION:
111
END DESCRIPTION:
XS GIS Cut Line= 3
      1512858.27      6787460.49      1512605.52      6787417.95
      1512219.34      6787383.68
#Sta/Elev= 30
  4743.7 2275.88  4785.7 2272.25  4818.0 2256.92  4846.2 2247.54  4851.3 2249.38
  4858.6 2246.57  4899.1 2241.90  4906.8 2242.47  4911.8 2239.64  4919.4 2233.07
  4929.5 2228.83  4949.8 2214.95  4960.0 2204.12  4964.7 2196.50  4965.1 2196.00
  4969.9 2196.50  4990.4 2199.84  4997.7 2202.65  5030.6 2203.70  5040.7 2205.83
  5055.9 2212.14  5060.9 2210.95  5070.8 2212.42  5161.2 2212.26  5211.4 2215.55
  5271.6 2222.24  5279.4 2224.22  5284.4 2223.44  5341.9 2235.99  5387.7 2240.11
#Mann=3,-1,0
  4743.7    0.16       0  4964.7    0.07       0  4969.9    0.16       0
Bank Sta=4964.7,4969.9
Exp/Cntr=0.3,0.1

Type RM Length L Ch R = 1,6197,252,252,252
BEGIN DESCRIPTION:
110
END DESCRIPTION:
XS GIS Cut Line= 3
      1512555.00      6787138.00      1512450.82      6787189.71
      1512355.00      6787238.00
#Sta/Elev= 30
  4883.7 2231.08  4886.5 2231.08  4892.1 2227.12  4897.7 2225.98  4906.0 2222.49
  4914.5 2219.46  4920.1 2218.37  4936.9 2213.20  4950.7 2207.99  4959.3 2203.72
  4967.4 2200.08  4981.8 2197.56  4987.3 2195.27  4992.3 2192.40  4992.7 2191.90
  4997.1 2191.90  4997.5 2192.40  5004.1 2192.52  5009.7 2194.37  5017.7 2197.89
  5026.4 2198.52  5040.1 2203.41  5048.7 2203.39  5054.3 2204.10  5062.5 2203.84
  5076.6 2207.97  5084.9 2210.09  5093.4 2210.54  5104.5 2212.23  5107.3 2212.23
#Mann=3,-1,0
  4883.7    0.16       0  4992.3    0.07       0  4997.5    0.16       0
Bank Sta=4992.3,4997.5
Exp/Cntr=0.3,0.1

Type RM Length L Ch R = 1,5945,246,246,246
BEGIN DESCRIPTION:
848
END DESCRIPTION:
XS GIS Cut Line= 2
      1512590.48      6786988.51      1512139.90      6787020.31
#Sta/Elev= 30
  4713.4 2235.00  4718.9 2232.14  4728.9 2229.75  4738.9 2226.16  4775.6 2218.44
  4780.6 2219.13  4799.1 2215.99  4839.2 2211.61  4849.2 2211.32  4859.2 2209.89
  4909.4 2206.83  4921.8 2206.77  4949.5 2198.57  4969.5 2195.02  4979.5 2191.51
  4986.9 2190.79  4987.3 2190.29  4991.8 2190.29  4992.2 2190.79  5009.6 2196.98
  5029.7 2209.00  5039.7 2214.10  5058.0 2216.76  5063.0 2216.52  5069.8 2217.56
  5079.8 2217.54  5099.8 2219.72  5109.9 2222.17  5150.0 2228.59  5165.1 2232.16
#Mann=3,-1,0
  4713.4    0.16       0  4986.9    0.07       0  4992.2    0.16       0
Bank Sta=4986.9,4992.2
Exp/Cntr=0.3,0.1

Type RM Length L Ch R = 1,5699,446,446,446
BEGIN DESCRIPTION:
109
END DESCRIPTION:
XS GIS Cut Line= 3
      1512455.02      6786838.01      1512359.15      6786782.65
      1512254.99      6786788.00
#Sta/Elev= 30
  4889.3 2213.50  4897.2 2213.59  4912.4 2211.27  4918.7 2210.42  4924.5 2207.84
  4934.5 2204.82  4940.3 2201.81  4947.1 2197.94  4956.1 2194.80  4961.8 2193.72
  4970.2 2191.34  4977.6 2187.86  4980.7 2187.84  4981.1 2187.34  4985.6 2187.34
  4986.0 2187.84  4993.2 2191.28  4999.2 2192.41  5003.4 2192.64  5008.0 2191.71
  5014.2 2192.65  5034.2 2196.39  5054.2 2200.41  5064.2 2204.12  5067.7 2204.88
  5074.2 2206.30  5084.3 2207.48  5094.3 2209.74  5101.8 2210.85  5104.3 2210.85
#Mann=4,-1,0
  4889.3    0.16       0  4980.7    0.07       0  4986.0    0.16       0
  5067.7    0.07       0
Bank Sta=4980.7,4986
Exp/Cntr=0.3,0.1

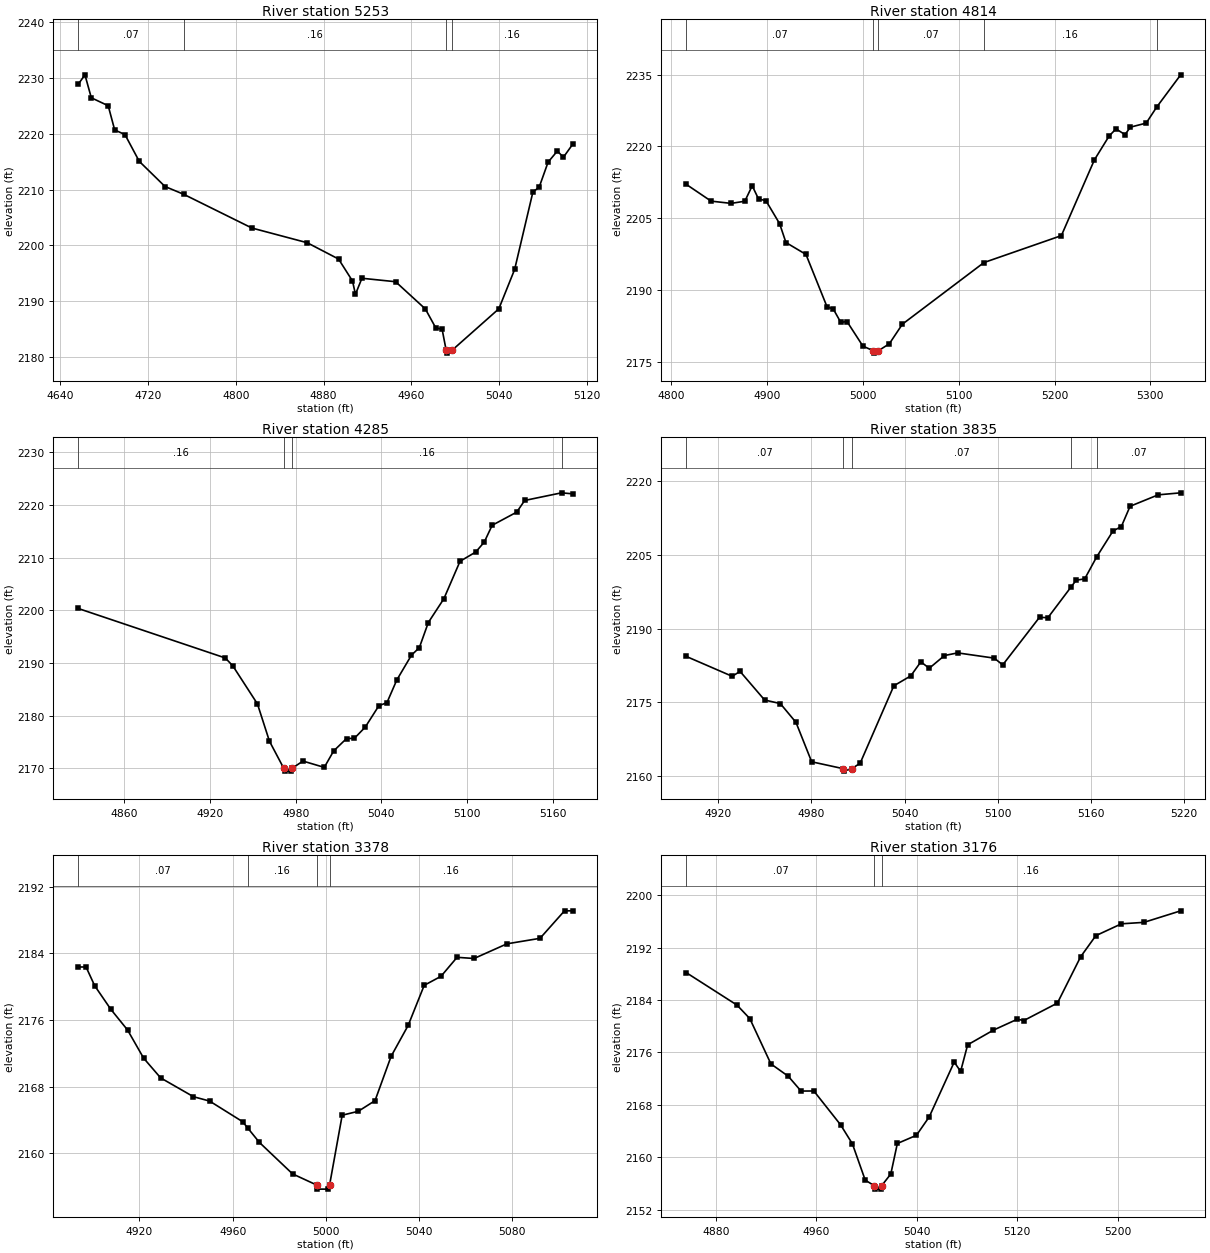
Type RM Length L Ch R = 1,5253,439,439,439
BEGIN DESCRIPTION:
108
END DESCRIPTION:
XS GIS Cut Line= 3
      1512692.24      6786618.12      1512400.53      6786436.36
      1512304.98      6786387.99
#Sta/Elev= 30
  4656.3 2228.83  4662.5 2230.54  4668.3 2226.43  4683.7 2225.01  4689.6 2220.68
  4699.0 2219.84  4712.0 2215.06  4735.5 2210.55  4752.4 2209.17  4814.7 2203.12
  4865.1 2200.49  4893.7 2197.57  4906.4 2193.64  4909.1 2191.26  4915.0 2194.13
  4945.7 2193.51  4972.8 2188.64  4982.3 2185.25  4988.1 2185.00  4991.8 2181.23
  4992.2 2180.73  4997.1 2181.23  5039.8 2188.66  5054.2 2195.70  5070.9 2209.60
  5076.5 2210.39  5084.7 2214.91  5093.1 2216.89  5098.7 2215.80  5107.1 2218.10
#Mann=4,-1,0
  4656.3    0.07       0  4752.4    0.16       0  4991.8    0.07       0
  4997.1    0.16       0
Bank Sta=4991.8,4997.1
Exp/Cntr=0.3,0.1

Type RM Length L Ch R = 1,4814,529,529,529
BEGIN DESCRIPTION:
107
END DESCRIPTION:
XS GIS Cut Line= 3
      1512790.59      6786209.20      1512649.53      6786090.45
      1512355.04      6785938.02
#Sta/Elev= 30
  4815.6 2212.10  4841.6 2208.58  4862.5 2208.11  4876.8 2208.56  4884.5 2211.79
  4891.1 2209.03  4898.8 2208.68  4913.1 2203.87  4919.7 2199.93  4940.6 2197.44
  4962.6 2186.48  4969.1 2186.03  4976.9 2183.24  4983.4 2183.42  5000.0 2178.28
  5010.8 2177.31  5011.2 2176.81  5016.2 2177.31  5027.6 2178.77  5041.2 2182.86
  5126.3 2195.74  5207.1 2201.37  5241.6 2217.22  5257.0 2222.21  5264.1 2223.68
  5273.5 2222.48  5279.1 2224.04  5295.6 2224.89  5306.6 2228.25  5331.6 2234.98
#Mann=5,-1,0
  4815.6    0.07       0  5010.8    0.07       0  5016.2    0.07       0
  5126.3    0.16       0  5306.6    0.07       0
Bank Sta=5010.8,5016.2
Exp/Cntr=0.3,0.1

Type RM Length L Ch R = 1,4285,450,450,450
BEGIN DESCRIPTION:
106
END DESCRIPTION:
XS GIS Cut Line= 3
      1512925.87      6785886.38      1512868.16      6785723.93
      1512793.68      6785566.67
#Sta/Elev= 30
  4827.6 2200.36  4930.7 2190.95  4936.0 2189.43  4953.2 2182.22  4961.6 2175.14
  4971.7 2169.95  4972.2 2169.45  4976.8 2169.45  4977.2 2169.95  4985.1 2171.36
  5000.0 2170.16  5006.6 2173.29  5015.6 2175.64  5021.1 2175.68  5028.7 2177.81
  5038.3 2181.89  5043.9 2182.45  5050.8 2186.76  5061.1 2191.49  5066.6 2192.91
  5072.9 2197.69  5083.8 2202.21  5095.1 2209.32  5106.1 2211.08  5112.1 2212.98
  5117.6 2216.16  5134.8 2218.66  5140.4 2220.88  5166.2 2222.33  5174.0 2222.14
#Mann=4,-1,0
  4827.6    0.16       0  4971.7    0.07       0  4977.2    0.16       0
  5166.2    0.07       0
Bank Sta=4971.7,4977.2
Exp/Cntr=0.3,0.1

Type RM Length L Ch R = 1,3835,457,457,457
BEGIN DESCRIPTION:
105
END DESCRIPTION:
XS GIS Cut Line= 3
      1513254.97      6785488.00      1513155.46      6785473.19
      1512955.01      6785388.01
#Sta/Elev= 30
  4899.4 2184.33  4929.0 2180.28  4934.1 2181.27  4949.9 2175.45  4960.0 2174.73
  4970.1 2170.90  4980.2 2162.88  5000.5 2161.48  5000.9 2160.98  5006.0 2161.48
  5011.4 2162.58  5033.1 2178.34  5044.0 2180.36  5050.5 2183.22  5055.9 2181.91
  5065.7 2184.50  5074.2 2185.04  5097.8 2183.97  5103.2 2182.59  5126.9 2192.28
  5132.3 2192.20  5147.3 2198.49  5150.5 2199.83  5156.0 2200.10  5163.7 2204.57
  5174.2 2209.84  5179.6 2210.75  5185.2 2214.87  5203.3 2217.20  5217.8 2217.61
#Mann=5,-1,0
  4899.4    0.07       0  5000.5    0.07       0  5006.0    0.07       0
  5147.3    0.16       0  5163.7    0.07       0
Bank Sta=5000.5,5006
Exp/Cntr=0.3,0.1

Type RM Length L Ch R = 1,3378,202,202,202
BEGIN DESCRIPTION:
104
END DESCRIPTION:
XS GIS Cut Line= 3
      1513354.99      6785137.99      1513281.44      6785061.24
      1513204.97      6784987.98
#Sta/Elev= 30
  4893.7 2182.35  4897.1 2182.35  4900.8 2180.10  4907.7 2177.28  4914.9 2174.79
  4921.8 2171.41  4929.1 2169.04  4943.2 2166.78  4950.1 2166.26  4964.3 2163.78
  4966.6 2162.98  4971.5 2161.29  4985.7 2157.52  4996.0 2156.19  4996.4 2155.69
  5001.1 2155.69  5001.6 2156.19  5007.0 2164.56  5013.9 2165.03  5021.1 2166.31
  5028.0 2171.63  5035.3 2175.33  5042.2 2180.15  5049.4 2181.23  5056.3 2183.51
  5063.6 2183.37  5077.7 2185.13  5091.9 2185.79  5102.4 2189.09  5105.9 2189.09
#Mann=4,-1,0
  4893.7    0.07       0  4966.6    0.16       0  4996.0    0.07       0
  5001.6    0.16       0
Bank Sta=4996,5001.6
Exp/Cntr=0.3,0.1

Type RM Length L Ch R = 1,3176,290,290,290
BEGIN DESCRIPTION:
847
END DESCRIPTION:
XS GIS Cut Line= 2
      1513544.64      6784936.88      1513158.81      6784857.60
#Sta/Elev= 30
  4856.4 2188.18  4896.9 2183.22  4907.1 2181.16  4923.9 2174.25  4937.7 2172.37
  4947.9 2170.11  4958.1 2170.12  4979.4 2164.96  4988.8 2162.06  4999.0 2156.53
  5006.4 2155.65  5006.8 2155.15  5011.5 2155.15  5012.0 2155.65  5019.4 2157.46
  5024.6 2162.11  5039.8 2163.36  5050.0 2166.17  5069.9 2174.53  5075.0 2173.11
  5080.6 2177.16  5101.1 2179.40  5120.2 2181.07  5125.3 2180.86  5152.1 2183.53
  5170.6 2190.59  5182.7 2193.81  5203.1 2195.62  5221.0 2195.84  5250.3 2197.60
#Mann=3,-1,0
  4856.4    0.07       0  5006.4    0.07       0  5012.0    0.16       0
Bank Sta=5006.4,5012
Exp/Cntr=0.3,0.1