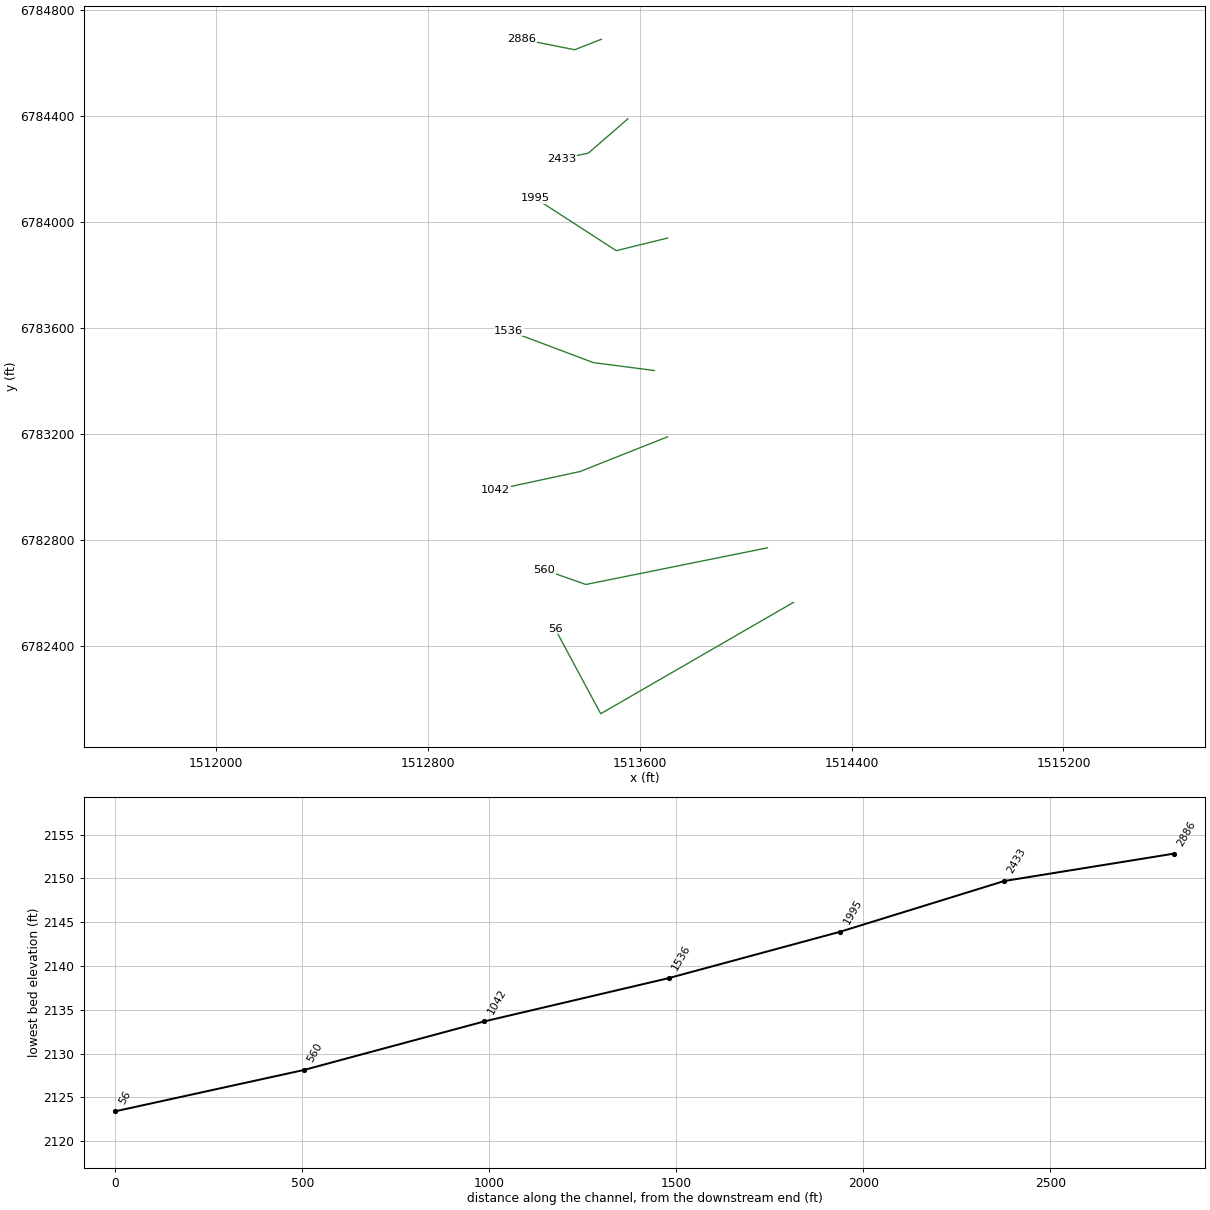
HEC-RAS study Elm 49.prj: Elm 49 Base Level Engineering

--- Elm 49.g01 (geometry) --- (continued)

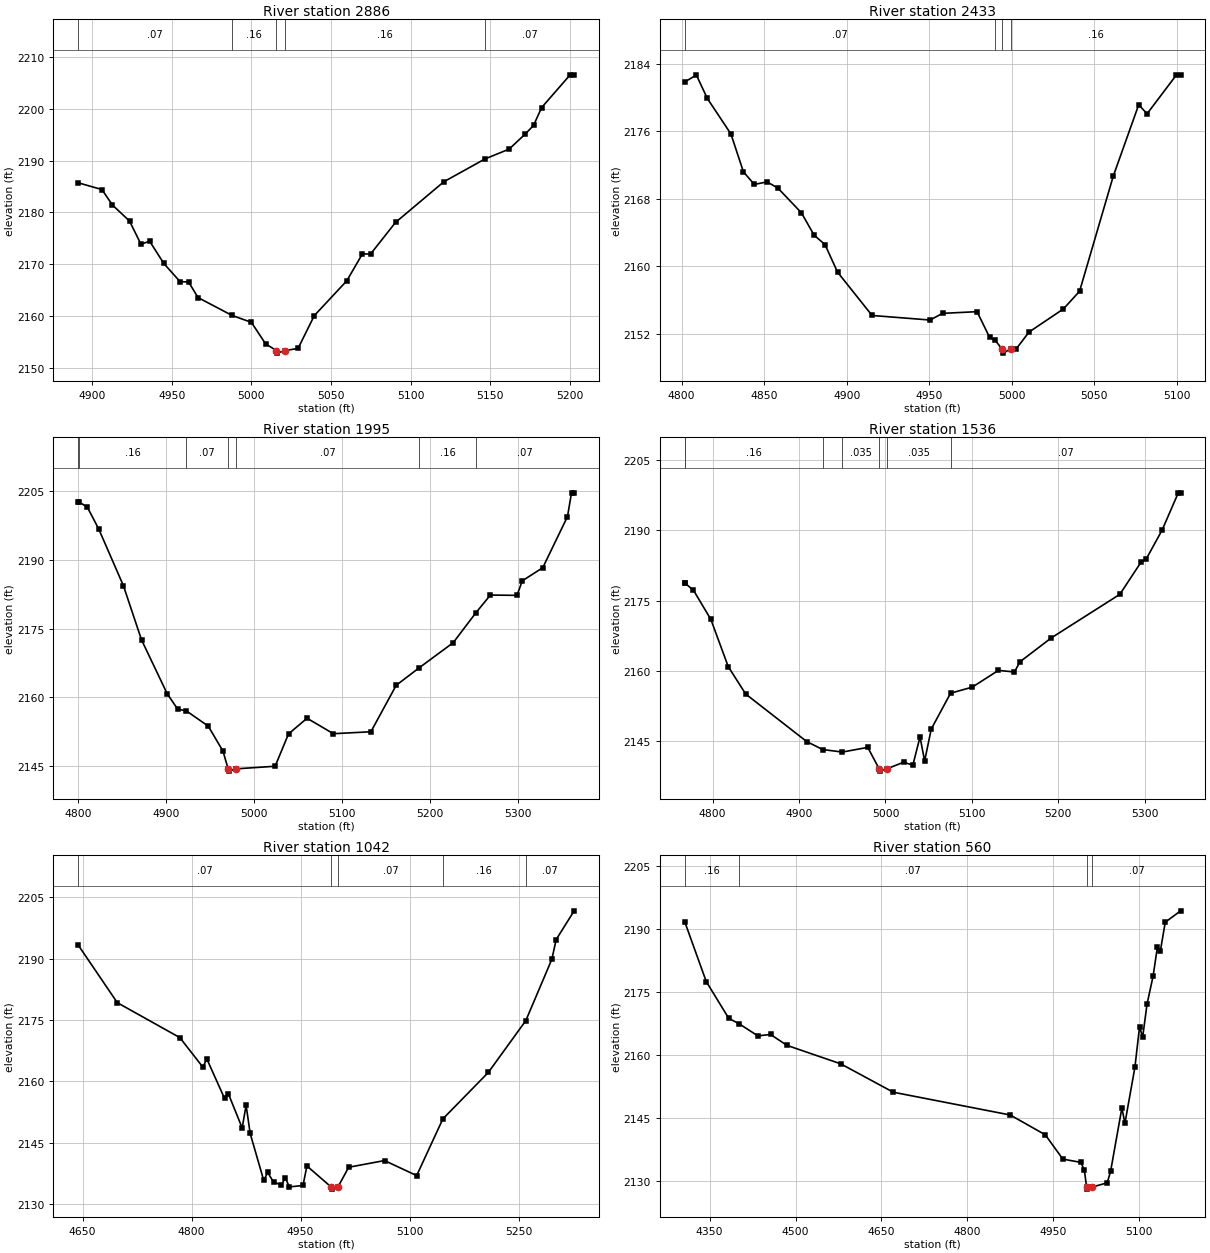
Type RM Length L Ch R = 1,2886,453,453,453
BEGIN DESCRIPTION:
103
END DESCRIPTION:
XS GIS Cut Line= 3
      1513455.02      6784688.01      1513353.74      6784648.51
      1513155.03      6784687.99
#Sta/Elev= 30
  4891.3 2185.73  4906.2 2184.42  4912.8 2181.43  4923.5 2178.34  4930.7 2173.85
  4936.1 2174.46  4945.0 2170.16  4955.2 2166.64  4960.6 2166.56  4966.5 2163.56
  4987.8 2160.11  5000.0 2158.77  5008.9 2154.62  5015.7 2153.32  5016.2 2152.82
  5021.3 2153.32  5029.3 2153.73  5039.5 2160.07  5059.9 2166.80  5069.7 2172.00
  5074.8 2171.96  5090.5 2178.08  5120.8 2185.93  5146.7 2190.35  5161.8 2192.24
  5172.0 2195.18  5177.1 2196.81  5182.2 2200.27  5200.1 2206.59  5202.6 2206.59
#Mann=5,-1,0
  4891.3    0.07       0  4987.8    0.16       0  5015.7    0.07       0
  5021.3    0.16       0  5146.7    0.07       0
Bank Sta=5015.7,5021.3
Exp/Cntr=0.3,0.1

Type RM Length L Ch R = 1,2433,438,438,438
BEGIN DESCRIPTION:
102
END DESCRIPTION:
XS GIS Cut Line= 3
      1513554.99      6784387.99      1513405.29      6784258.25
      1513305.01      6784238.00
#Sta/Elev= 30
  4801.9 2181.82  4809.0 2182.63  4815.6 2179.87  4829.9 2175.66  4837.5 2171.16
  4844.1 2169.68  4851.8 2169.98  4858.4 2169.24  4872.6 2166.32  4880.3 2163.67
  4886.9 2162.55  4894.5 2159.29  4915.4 2154.16  4950.5 2153.62  4958.1 2154.41
  4979.0 2154.61  4986.6 2151.57  4990.0 2151.21  4994.1 2150.20  4994.5 2149.70
  4999.7 2150.20  5002.7 2150.20  5010.5 2152.20  5031.3 2154.93  5041.1 2157.03
  5061.5 2170.66  5076.9 2179.11  5082.0 2178.05  5099.8 2182.66  5102.3 2182.66
#Mann=4,-1,0
  4801.9    0.07       0  4990.0    0.16       0  4994.1    0.07       0
  4999.7    0.16       0
Bank Sta=4994.1,4999.7
Exp/Cntr=0.3,0.1

Type RM Length L Ch R = 1,1995,459,459,459
BEGIN DESCRIPTION:
101
END DESCRIPTION:
XS GIS Cut Line= 3
      1513704.96      6783937.99      1513510.95      6783890.25
      1513204.99      6784088.00
#Sta/Elev= 30
  4800.2 2202.54  4801.5 2202.54  4810.5 2201.48  4823.5 2196.71  4851.6 2184.34
  4872.2 2172.54  4901.4 2160.79  4913.4 2157.41  4923.2 2157.05  4948.1 2153.73
  4964.9 2148.26  4970.7 2144.42  4971.2 2143.92  4979.7 2144.42  5024.2 2144.98
  5039.4 2152.03  5060.5 2155.45  5090.4 2152.08  5133.1 2152.50  5161.9 2162.63
  5188.0 2166.44  5226.7 2171.91  5252.6 2178.45  5269.0 2182.30  5299.3 2182.23
  5305.3 2185.40  5328.6 2188.26  5356.7 2199.40  5361.3 2204.58  5364.3 2204.58
#Mann=7,-1,0
  4800.2    0.07       0  4801.5    0.16       0  4923.2    0.07       0
  4970.7    0.07       0  4979.7    0.07       0  5188.0    0.16       0
  5252.6    0.07       0
Bank Sta=4970.7,4979.7
Exp/Cntr=0.3,0.1

Type RM Length L Ch R = 1,1536,494,494,494
BEGIN DESCRIPTION:
100
END DESCRIPTION:
XS GIS Cut Line= 3
      1513655.00      6783438.00      1513424.63      6783467.86
      1513104.96      6783588.01
#Sta/Elev= 30
  4767.7 2178.74  4768.1 2178.74  4777.8 2177.26  4798.0 2171.01  4818.1 2160.93
  4838.3 2155.08  4908.9 2144.93  4927.4 2143.23  4950.1 2142.69  4979.5 2143.69
  4992.7 2139.12  4993.2 2138.62  5001.8 2139.12  5021.0 2140.52  5031.7 2139.90
  5040.0 2145.93  5045.3 2140.79  5053.0 2147.61  5075.3 2155.25  5100.5 2156.56
  5130.7 2160.13  5149.2 2159.79  5155.6 2161.96  5191.9 2167.07  5271.2 2176.37
  5296.1 2183.35  5301.4 2183.81  5320.1 2190.09  5338.8 2198.04  5341.5 2198.04
#Mann=7,-1,0
  4767.7    0.07       0  4768.1    0.16       0  4927.4    0.07       0
  4950.1   0.035       0  4992.7   0.035       0  5001.8   0.035       0
  5075.3    0.07       0
Bank Sta=4992.7,5001.8
Exp/Cntr=0.3,0.1

Type RM Length L Ch R = 1,1042,482,482,482
BEGIN DESCRIPTION:
99
END DESCRIPTION:
XS GIS Cut Line= 3
      1513705.00      6783188.00      1513374.04      6783056.82
      1513054.98      6782988.00
#Sta/Elev= 30
  4644.0 2193.32  4697.8 2179.24  4783.8 2170.71  4815.6 2163.47  4820.9 2165.51
  4845.3 2155.87  4850.6 2156.99  4869.6 2148.62  4875.0 2154.19  4880.6 2147.28
  4899.3 2135.78  4904.7 2137.75  4912.9 2135.35  4923.6 2134.71  4929.0 2136.47
  4934.4 2134.21  4953.3 2134.56  4958.7 2139.33  4992.2 2134.17  4992.7 2133.67
  5001.3 2134.17  5016.2 2139.02  5065.5 2140.65  5109.7 2136.98  5145.8 2150.85
  5208.3 2162.19  5259.9 2174.86  5295.7 2189.85  5301.7 2194.68  5326.4 2201.69
#Mann=5,-1,0
  4644.0    0.07       0  4992.2    0.07       0  5001.3    0.07       0
  5145.8    0.16       0  5259.9    0.07       0
Bank Sta=4992.2,5001.3
Exp/Cntr=0.3,0.1

Type RM Length L Ch R = 1,560,504,504,504
BEGIN DESCRIPTION:
784
END DESCRIPTION:
XS GIS Cut Line= 3
      1514081.84      6782768.94      1513396.25      6782630.60
      1513239.72      6782685.84
#Sta/Elev= 30
  4306.6 2191.68  4344.2 2177.45  4383.5 2168.70  4401.3 2167.43  4434.3 2164.54
  4456.4 2164.87  4485.1 2162.28  4578.8 2157.90  4670.6 2151.15  4874.7 2145.74
  4935.9 2141.03  4966.5 2135.26  4998.0 2134.48  5004.1 2132.58  5007.9 2128.63
  5008.4 2128.13  5017.9 2128.63  5043.9 2129.63  5049.8 2132.35  5069.5 2147.40
  5074.8 2143.78  5092.2 2157.04  5100.4 2166.76  5105.7 2164.17  5113.4 2172.08
  5124.0 2178.74  5131.4 2185.55  5136.7 2184.75  5145.2 2191.53  5172.0 2194.24
#Mann=4,-1,0
  4306.6    0.16       0  4401.3    0.07       0  5007.9    0.07       0
  5017.9    0.07       0
Bank Sta=5007.9,5017.9
Exp/Cntr=0.3,0.1

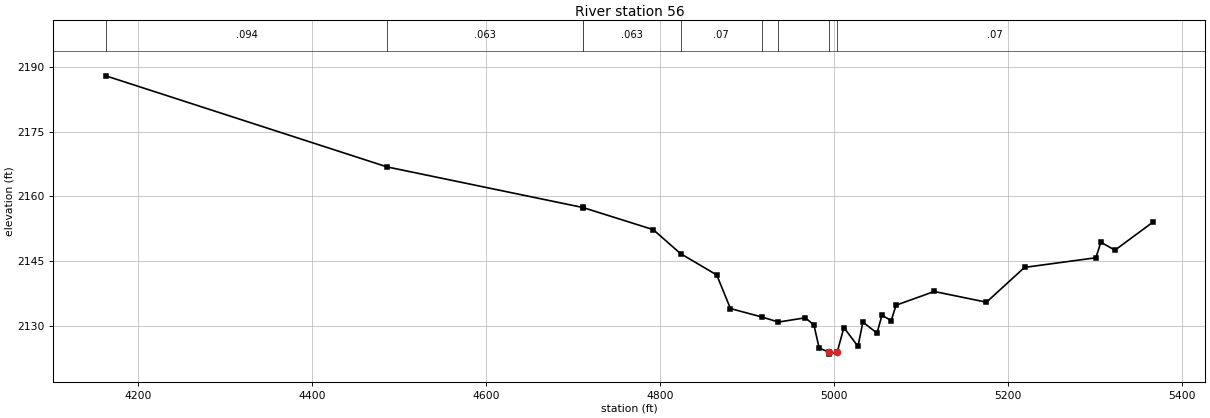
Type RM Length L Ch R = 1,56,0,0,0
BEGIN DESCRIPTION:
98
END DESCRIPTION:
XS GIS Cut Line= 3
      1514180.03      6782563.01      1513452.20      6782142.93
      1513280.01      6782462.99
#Sta/Elev= 30
  4162.6 2187.97  4486.0 2166.84  4710.9 2157.43  4711.1 2157.42  4791.9 2152.29
  4823.3 2146.73  4864.9 2141.78  4880.6 2133.99  4916.8 2132.03  4935.8 2130.86
  4966.8 2131.85  4976.6 2130.16  4982.6 2124.83  4993.4 2123.92  4993.9 2123.42
  5003.4 2123.92  5011.0 2129.59  5027.2 2125.23  5032.9 2130.85  5049.1 2128.29
  5054.8 2132.45  5065.4 2131.18  5071.0 2134.77  5114.9 2137.95  5174.9 2135.46
  5218.7 2143.54  5300.7 2145.77  5306.4 2149.38  5322.6 2147.53  5366.4 2154.06
#Mann=9,-1,0
  4162.6   0.094       0  4486.0   0.063       0  4710.9   0.035       0
  4711.1   0.063       0  4823.3    0.07       0  4916.8   0.035       0
  4935.8    0.07       0  4993.4    0.07       0  5003.4    0.07       0
Bank Sta=4993.4,5003.4
Exp/Cntr=0.3,0.1

Chan Stop Cuts=-1