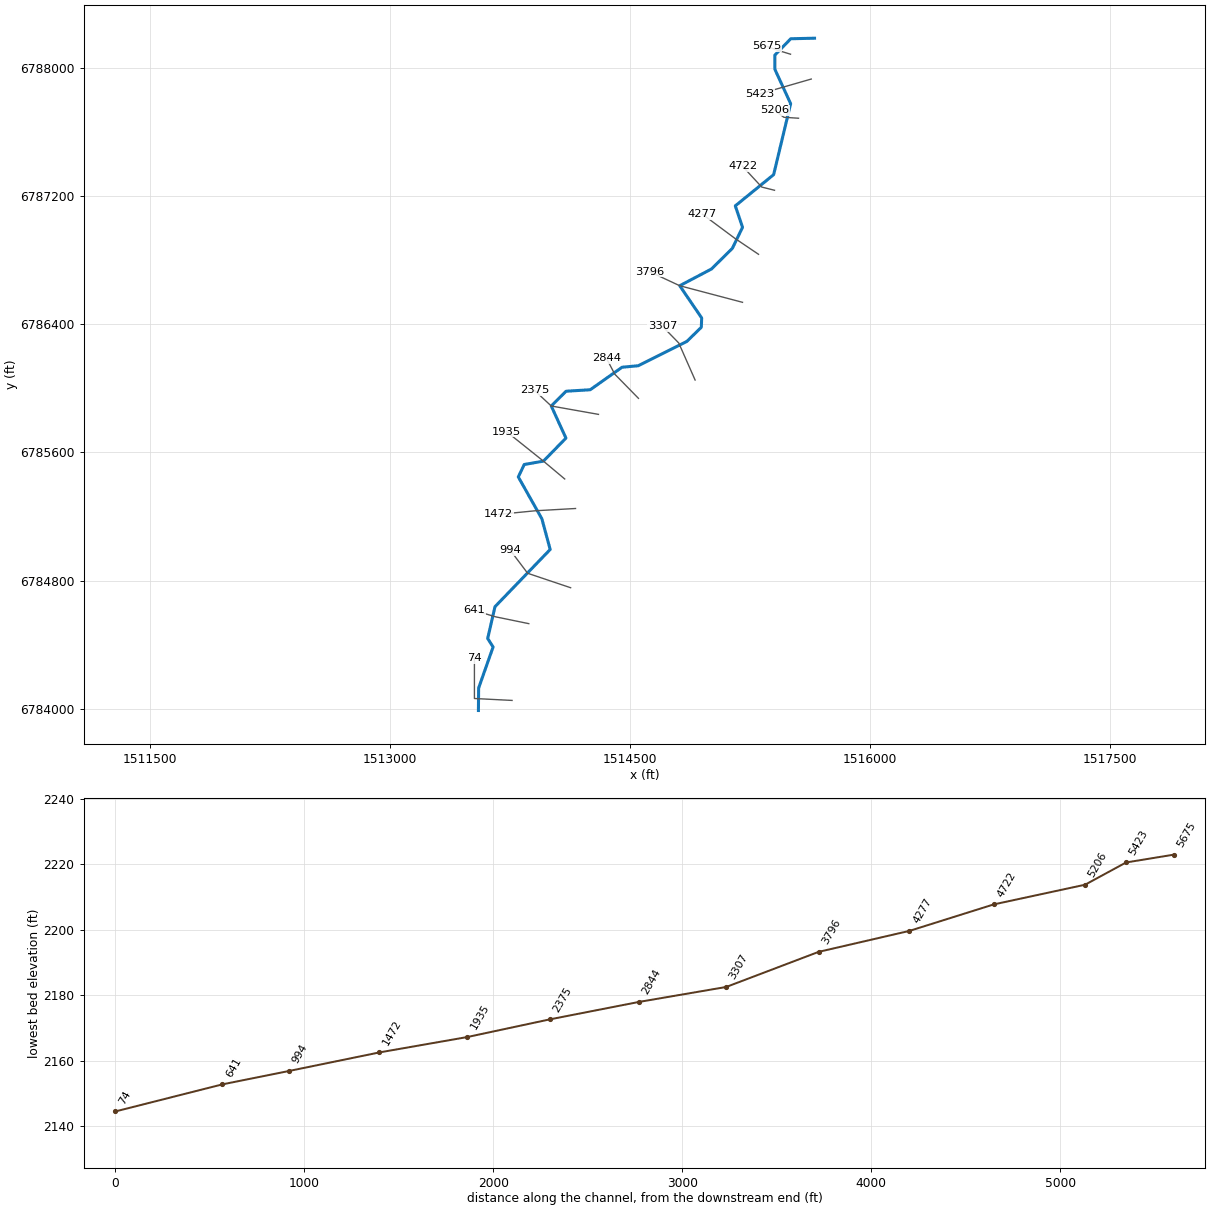
--- Elm 50.prj (project) ---

Proj Title=Elm 50 Base Level Engineering
Current Plan=p01
Default Exp/Contr=0.3,0.1
English Units
Geom File=g01
Flow File=f01
Plan File=p01
BEGIN DESCRIPTION:
Elm 50
END DESCRIPTION:

--- Elm 50.p01 (plan) ---

Plan Title=Multiple Run
Short Identifier=Multiple
Geom File=g01
Flow File=f01
Subcritical Flow
K Sum by GR= 0
Std Step Tol= 0.01
Critical Tol= 0.01
Num of Std Step Trials= 20
Max Error Tol= 0.3
Flow Tol Ratio= 0.001
Split Flow NTrial= 30
Split Flow Tol= 0.02
Split Flow Ratio= 0.02
Log Output Level= 0
Friction Slope Method= 1
Unsteady Friction Slope Method= 2
Unsteady Bridges Friction Slope Method= 1
Parabolic Critical Depth
Global Vel Dist=  1 , 1 , 1
Global Log Level= 0
CheckData=True
Encroach Param= -1, 0, 0, 0
BEGIN DESCRIPTION:
Multiple Run
END DESCRIPTION:

--- Elm 50.f01 (steady flow) ---

Flow Title=Multiple
Number of Profiles=7
Profile Names=10-year,25-year,50-year,1pct_min,100-year,1pct_plu,500-year
River Rch & RM= Elm 50,Reach-1,5675
     275     386     479     369     591     813     912
River Rch & RM= Elm 50,Reach-1,5423
     377     539     677     528     847    1160    1340
Boundary for River Rch & Prof#=Elm 50,Reach-1,1
Up Type=0
Dn Type=3
Dn Slope=0.005
Boundary for River Rch & Prof#=Elm 50,Reach-1,2
Up Type=0
Dn Type=3
Dn Slope=0.005
Boundary for River Rch & Prof#=Elm 50,Reach-1,3
Up Type=0
Dn Type=3
Dn Slope=0.005
Boundary for River Rch & Prof#=Elm 50,Reach-1,4
Up Type=0
Dn Type=3
Dn Slope=0.005
Boundary for River Rch & Prof#=Elm 50,Reach-1,5
Up Type=0
Dn Type=3
Dn Slope=0.005
Boundary for River Rch & Prof#=Elm 50,Reach-1,6
Up Type=0
Dn Type=3
Dn Slope=0.005
Boundary for River Rch & Prof#=Elm 50,Reach-1,7
Up Type=0
Dn Type=3
Dn Slope=0.005

--- Elm 50.g01 (geometry) ---

Geom Title=Existing Conditions

River Reach=Elm 50,Reach-1
Reach XY= 30
      1515655.00      6788188.00      1515506.44      6788184.51
      1515407.07      6788082.53      1515407.26      6787993.56
      1515505.78      6787778.86      1515399.53      6787335.55
      1515159.99      6787140.55      1515205.18      6787006.43
      1515141.38      6786874.78      1515011.06      6786746.14
      1514812.67      6786641.66      1514949.92      6786440.28
      1514947.55      6786381.93      1514857.31      6786293.83
      1514553.41      6786141.83      1514452.58      6786132.46
      1514253.44      6785991.76      1514102.53      6785982.54
      1514010.06      6785890.30      1514101.90      6785689.65
      1513961.17      6785545.86      1513841.27      6785524.77
      1513804.13      6785447.20      1513951.18      6785186.42
      1514003.38      6784994.03      1513658.54      6784636.53
      1513612.79      6784437.90      1513646.72      6784384.78
      1513556.33      6784128.36      1513555.00      6783988.00

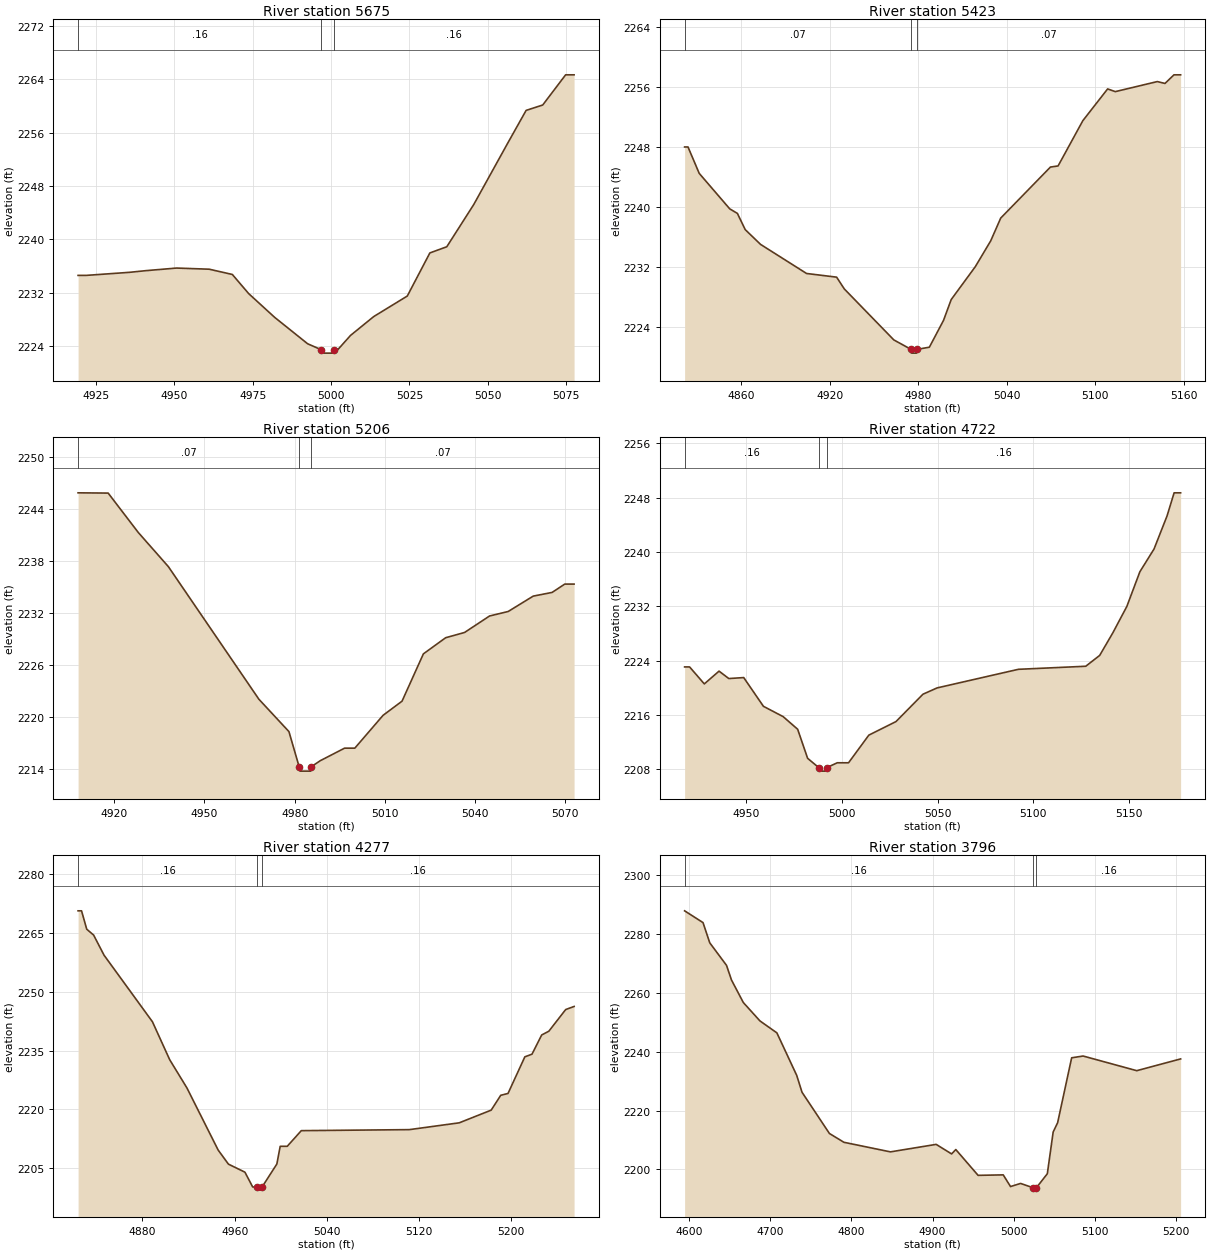
Type RM Length L Ch R = 1,5675,252,252,252
BEGIN DESCRIPTION:
333
END DESCRIPTION:
XS GIS Cut Line= 3
      1515505.00      6788088.00      1515427.82      6788111.58
      1515354.97      6788138.01
#Sta/Elev= 26
  4919.3 2234.58  4921.9 2234.58  4935.7 2235.04  4940.9 2235.29  4950.7 2235.68
  4961.1 2235.51  4968.5 2234.72  4973.7 2231.85  4982.0 2228.28  4992.5 2224.32
  4996.9 2223.41  4997.1 2222.91  5000.6 2222.91  5000.9 2223.41  5002.1 2223.41
  5006.2 2225.57  5013.6 2228.40  5024.3 2231.48  5031.5 2237.95  5036.9 2238.88
  5045.5 2245.22  5056.2 2254.32  5062.2 2259.35  5067.5 2260.16  5074.8 2264.69
  5077.5 2264.69
#Mann=3,-1,0
  4919.3    0.16       0  4996.9    0.07       0  5000.9    0.16       0
Bank Sta=4996.9,5000.9
Exp/Cntr=0.3,0.1

Type RM Length L Ch R = 1,5423,217,217,217
BEGIN DESCRIPTION:
853
END DESCRIPTION:
XS GIS Cut Line= 2
      1515634.48      6787932.88      1515311.25      6787839.64
#Sta/Elev= 30
  4821.6 2248.02  4823.9 2248.02  4831.5 2244.50  4852.2 2239.77  4857.4 2239.16
  4862.7 2237.00  4873.1 2235.03  4904.3 2231.15  4924.7 2230.66  4929.9 2229.09
  4963.5 2222.29  4975.2 2221.03  4975.4 2220.53  4978.9 2220.53  4979.2 2221.03
  4987.6 2221.32  4997.2 2224.90  5002.4 2227.67  5018.8 2232.07  5029.2 2235.50
  5036.0 2238.54  5069.7 2245.34  5074.9 2245.49  5091.7 2251.53  5108.5 2255.76
  5113.7 2255.40  5142.2 2256.74  5147.4 2256.49  5153.5 2257.64  5158.0 2257.64
#Mann=3,-1,0
  4821.6    0.07       0  4975.2    0.07       0  4979.2    0.07       0
Bank Sta=4975.2,4979.2
Exp/Cntr=0.3,0.1

Type RM Length L Ch R = 1,5206,484,484,484
BEGIN DESCRIPTION:
332
END DESCRIPTION:
XS GIS Cut Line= 3
      1515554.95      6787688.00      1515463.15      6787694.06
      1515404.99      6787738.01
#Sta/Elev= 24
  4908.0 2245.85  4918.0 2245.82  4928.0 2241.28  4938.0 2237.34  4968.1 2222.04
  4978.1 2218.30  4981.5 2214.24  4981.8 2213.74  4985.3 2213.74  4985.5 2214.24
  4988.5 2214.94  4996.6 2216.39  5000.0 2216.39  5009.4 2220.18  5015.7 2221.81
  5022.8 2227.27  5030.2 2229.13  5036.5 2229.74  5044.8 2231.64  5051.0 2232.16
  5059.3 2233.93  5065.6 2234.36  5069.8 2235.32  5072.9 2235.32
#Mann=3,-1,0
  4908.0    0.07       0  4981.5    0.07       0  4985.5    0.07       0
Bank Sta=4981.5,4985.5
Exp/Cntr=0.3,0.1

Type RM Length L Ch R = 1,4722,445,445,445
BEGIN DESCRIPTION:
331
END DESCRIPTION:
XS GIS Cut Line= 3
      1515404.99      6787238.00      1515325.17      6787258.05
      1515205.00      6787388.00
#Sta/Elev= 30
  4917.7 2223.07  4920.3 2223.07  4928.0 2220.57  4935.7 2222.45  4940.8 2221.36
  4948.6 2221.50  4958.9 2217.27  4969.2 2215.75  4976.8 2213.89  4982.0 2209.61
  4987.9 2208.22  4988.1 2207.72  4991.6 2207.72  4991.9 2208.22  4997.5 2208.95
  5003.4 2208.95  5014.0 2213.02  5028.2 2215.02  5042.3 2219.05  5049.7 2219.98
  5092.2 2222.72  5127.4 2223.17  5134.7 2224.77  5141.6 2228.11  5148.9 2231.99
  5155.7 2237.09  5163.1 2240.44  5169.9 2245.31  5173.6 2248.72  5177.0 2248.72
#Mann=3,-1,0
  4917.7    0.16       0  4987.9    0.07       0  4991.9    0.16       0
Bank Sta=4987.9,4991.9
Exp/Cntr=0.3,0.1

Type RM Length L Ch R = 1,4277,481,481,481
BEGIN DESCRIPTION:
330
END DESCRIPTION:
XS GIS Cut Line= 3
      1515305.02      6786837.99      1515159.25      6786936.26
      1514955.04      6787087.97
#Sta/Elev= 30
  4824.2 2270.72  4827.2 2270.72  4831.7 2266.03  4837.7 2264.52  4846.7 2259.40
  4888.7 2242.39  4903.7 2232.68  4918.6 2225.50  4945.7 2209.63  4954.6 2206.04
  4968.9 2203.99  4975.6 2200.23  4979.7 2200.16  4979.9 2199.66  4983.7 2200.16
  4996.6 2206.07  4999.5 2210.59  5005.6 2210.59  5017.8 2214.59  5111.5 2214.85
  5154.8 2216.59  5182.5 2219.83  5190.8 2223.62  5197.1 2224.09  5211.7 2233.44
  5217.9 2234.12  5226.3 2239.02  5232.5 2239.98  5247.1 2245.51  5254.4 2246.30
#Mann=3,-1,0
  4824.2    0.16       0  4979.7    0.07       0  4983.7    0.16       0
Bank Sta=4979.7,4983.7
Exp/Cntr=0.3,0.1

Type RM Length L Ch R = 1,3796,489,489,489
BEGIN DESCRIPTION:
329
END DESCRIPTION:
XS GIS Cut Line= 3
      1515205.00      6786538.00      1514812.67      6786641.66
      1514626.00      6786728.78
#Sta/Elev= 30
  4594.2 2287.96  4616.9 2283.95  4625.2 2277.08  4645.9 2269.40  4652.0 2264.43
  4666.6 2256.76  4687.1 2250.50  4708.0 2246.43  4732.5 2231.94  4739.0 2226.23
  4772.8 2212.19  4790.7 2209.19  4848.1 2205.93  4904.5 2208.48  4923.5 2205.23
  4928.7 2206.72  4956.2 2197.94  4987.2 2198.10  4996.2 2194.12  5008.6 2195.19
  5023.7 2193.75  5024.0 2193.25  5028.2 2193.75  5041.6 2198.50  5048.8 2212.69
  5054.3 2215.85  5071.6 2237.94  5085.7 2238.55  5151.9 2233.56  5206.0 2237.56
#Mann=3,-1,0
  4594.2    0.16       0  5023.7    0.07       0  5028.2    0.16       0
Bank Sta=5023.7,5028.2
Exp/Cntr=0.3,0.1

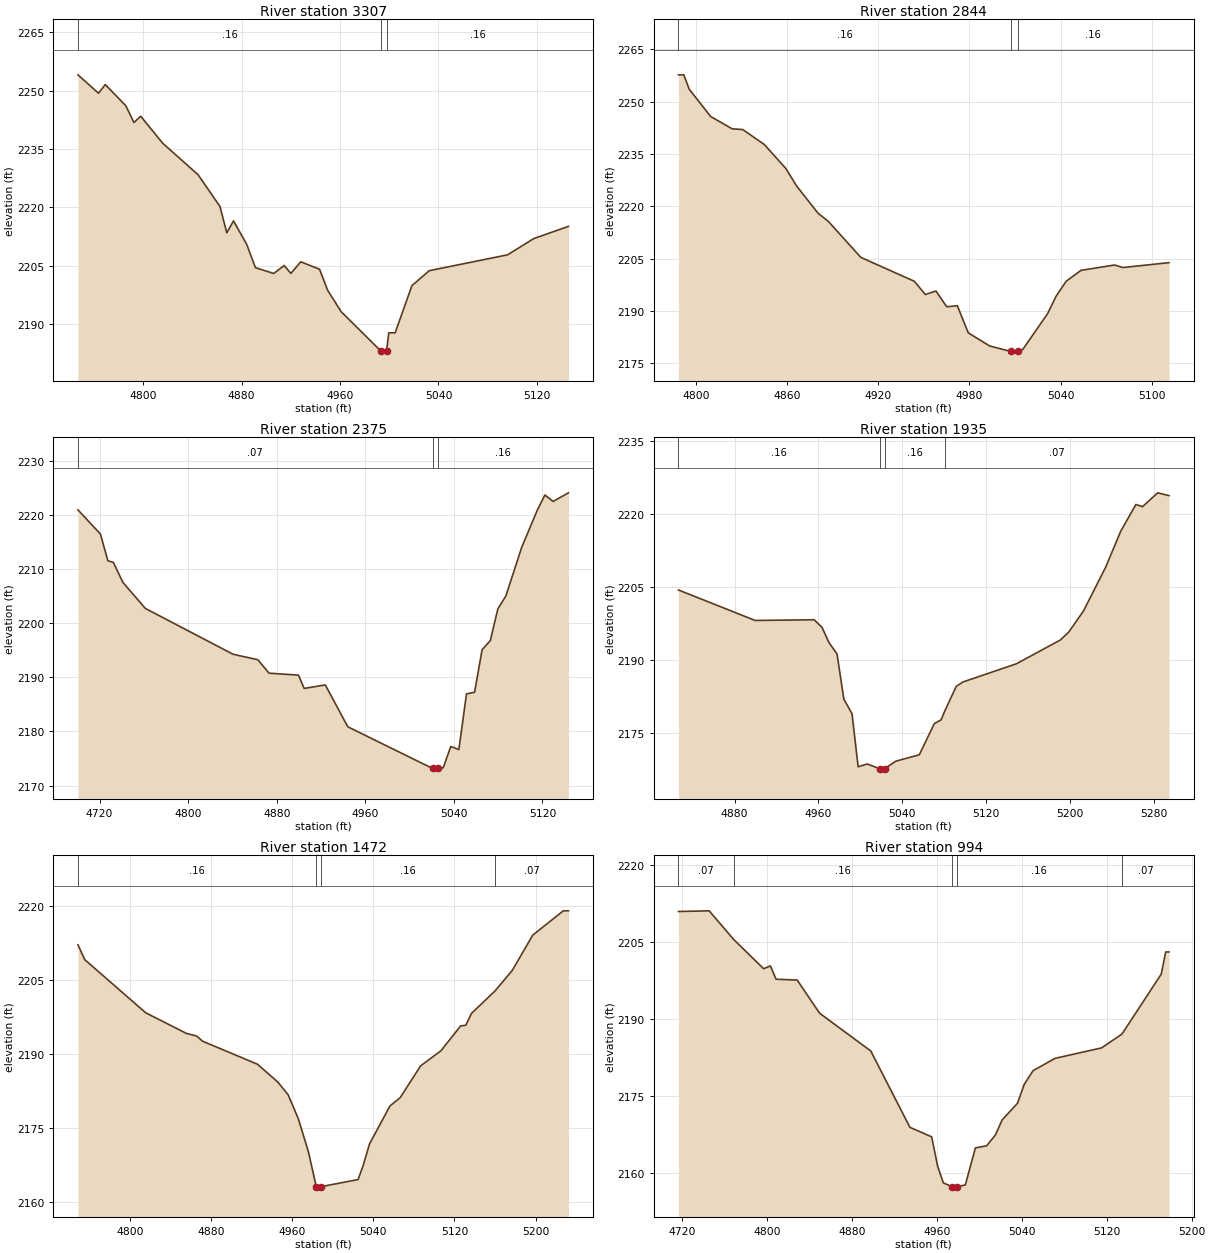
Type RM Length L Ch R = 1,3307,463,463,463
BEGIN DESCRIPTION:
328
END DESCRIPTION:
XS GIS Cut Line= 3
      1514908.84      6786052.44      1514806.74      6786283.81
      1514705.02      6786387.98
#Sta/Elev= 30
  4747.1 2254.07  4763.8 2249.34  4769.3 2251.57  4786.0 2246.12  4792.6 2241.81
  4798.1 2243.43  4815.9 2236.51  4844.7 2228.39  4862.5 2220.22  4868.0 2213.47
  4873.5 2216.52  4884.3 2210.43  4891.3 2204.50  4906.2 2203.01  4914.6 2205.06
  4920.1 2203.03  4928.1 2206.02  4943.4 2204.10  4949.9 2198.73  4960.9 2193.21
  4993.3 2183.04  4993.6 2182.54  4997.8 2183.04  4999.6 2187.76  5004.8 2187.76
  5018.4 2199.88  5032.5 2203.73  5096.1 2207.80  5117.4 2211.98  5145.6 2215.12
#Mann=3,-1,0
  4747.1    0.16       0  4993.3    0.07       0  4997.8    0.16       0
Bank Sta=4993.3,4997.8
Exp/Cntr=0.3,0.1

Type RM Length L Ch R = 1,2844,469,469,469
BEGIN DESCRIPTION:
327
END DESCRIPTION:
XS GIS Cut Line= 3
      1514555.01      6785937.99      1514406.81      6786089.31
      1514354.98      6786188.03
#Sta/Elev= 30
  4788.2 2257.67  4791.7 2257.67  4795.3 2253.54  4809.4 2245.74  4823.6 2242.20
  4830.6 2241.99  4844.7 2237.74  4858.9 2230.90  4866.0 2225.87  4880.2 2218.03
  4887.1 2215.64  4908.4 2205.38  4943.7 2198.53  4950.9 2194.75  4957.9 2195.75
  4965.0 2191.24  4972.0 2191.54  4979.2 2183.77  4993.3 2180.01  5007.1 2178.46
  5007.5 2177.96  5011.7 2178.46  5015.1 2179.00  5031.5 2189.27  5037.1 2194.26
  5043.7 2198.53  5053.5 2201.67  5075.6 2203.20  5081.2 2202.48  5111.5 2203.87
#Mann=3,-1,0
  4788.2    0.16       0  5007.1    0.07       0  5011.7    0.16       0
Bank Sta=5007.1,5011.7
Exp/Cntr=0.3,0.1

Type RM Length L Ch R = 1,2375,440,440,440
BEGIN DESCRIPTION:
326
END DESCRIPTION:
XS GIS Cut Line= 3
      1514304.96      6785838.01      1514010.06      6785890.30
      1513904.97      6785988.02
#Sta/Elev= 30
  4700.5 2220.98  4720.8 2216.52  4727.5 2211.57  4732.5 2211.27  4741.1 2207.57
  4761.4 2202.75  4840.6 2194.28  4863.0 2193.27  4873.1 2190.78  4899.7 2190.42
  4904.8 2187.96  4923.9 2188.61  4944.2 2180.87  5020.7 2173.17  5021.0 2172.67
  5025.4 2173.17  5030.4 2173.29  5037.2 2177.22  5044.5 2176.66  5051.4 2186.96
  5058.7 2187.25  5065.5 2195.12  5072.9 2196.80  5079.7 2202.66  5087.0 2205.08
  5101.2 2214.02  5115.4 2220.95  5122.2 2223.73  5129.6 2222.54  5143.5 2224.13
#Mann=3,-1,0
  4700.5    0.07       0  5020.7    0.07       0  5025.4    0.16       0
Bank Sta=5020.7,5025.4
Exp/Cntr=0.3,0.1

Type RM Length L Ch R = 1,1935,463,463,463
BEGIN DESCRIPTION:
325
END DESCRIPTION:
XS GIS Cut Line= 3
      1514094.16      6785434.44      1513961.17      6785545.86
      1513731.38      6785729.58
#Sta/Elev= 30
  4826.5 2204.47  4899.6 2198.21  4955.9 2198.35  4963.4 2196.78  4969.9 2193.71
  4977.7 2191.30  4984.2 2182.02  4992.0 2179.03  4997.8 2168.14  5006.5 2168.70
  5018.4 2167.74  5018.7 2167.24  5023.1 2167.74  5033.7 2169.28  5056.1 2170.60
  5070.5 2177.02  5076.9 2177.77  5080.6 2179.68  5091.3 2184.64  5097.7 2185.56
  5148.7 2189.30  5190.6 2194.19  5198.6 2195.81  5212.7 2200.17  5233.8 2209.15
  5248.2 2216.55  5262.6 2222.04  5269.0 2221.60  5283.4 2224.44  5294.2 2223.86
#Mann=4,-1,0
  4826.5    0.16       0  5018.4    0.07       0  5023.1    0.16       0
  5080.6    0.07       0
Bank Sta=5018.4,5023.1
Exp/Cntr=0.3,0.1

Type RM Length L Ch R = 1,1472,478,478,478
BEGIN DESCRIPTION:
324
END DESCRIPTION:
XS GIS Cut Line= 3
      1514161.74      6785249.99      1513911.14      6785235.83
      1513679.96      6785213.00
#Sta/Elev= 30
  4749.0 2212.12  4755.7 2209.11  4815.8 2198.33  4855.9 2194.15  4865.9 2193.62
  4871.9 2192.56  4926.0 2187.89  4946.1 2184.25  4956.1 2181.70  4966.1 2176.86
  4976.1 2170.13  4983.8 2163.07  4984.1 2162.57  4988.1 2162.57  4988.5 2163.07
  5025.0 2164.51  5030.0 2167.35  5036.3 2171.75  5056.4 2179.43  5066.5 2181.12
  5086.6 2187.56  5106.7 2190.64  5126.1 2195.68  5131.1 2195.79  5136.8 2198.22
  5159.8 2202.73  5177.0 2206.95  5197.1 2214.08  5227.2 2219.01  5232.3 2219.01
#Mann=4,-1,0
  4749.0    0.16       0  4983.8    0.07       0  4988.5    0.16       0
  5159.8    0.07       0
Bank Sta=4983.8,4988.5
Exp/Cntr=0.3,0.1

Type RM Length L Ch R = 1,994,353,353,353
BEGIN DESCRIPTION:
323
END DESCRIPTION:
XS GIS Cut Line= 3
      1514131.00      6784755.02      1513862.49      6784845.36
      1513755.00      6784987.99
#Sta/Elev= 30
  4716.7 2211.01  4745.6 2211.14  4768.8 2205.54  4796.9 2199.86  4803.3 2200.40
  4808.6 2197.81  4828.5 2197.65  4849.6 2191.19  4897.8 2183.83  4934.6 2168.96
  4955.1 2167.10  4960.8 2161.34  4966.1 2158.14  4973.9 2157.41  4974.2 2156.91
  4978.6 2157.41  4986.8 2157.71  4996.3 2164.94  5006.9 2165.35  5015.2 2167.47
  5021.4 2170.37  5036.0 2173.66  5042.3 2177.34  5050.6 2179.99  5071.4 2182.40
  5115.1 2184.43  5134.3 2187.12  5171.3 2198.81  5175.5 2203.13  5178.6 2203.13
#Mann=5,-1,0
  4716.7    0.07       0  4768.8    0.16       0  4973.9    0.07       0
  4978.6    0.16       0  5134.3    0.07       0
Bank Sta=4973.9,4978.6
Exp/Cntr=0.3,0.1

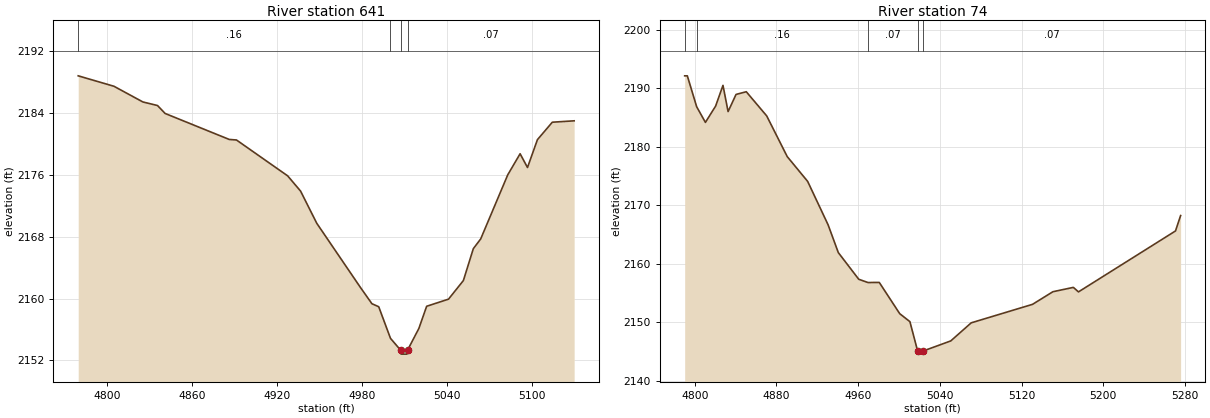
Type RM Length L Ch R = 1,641,567,567,567
BEGIN DESCRIPTION:
785
END DESCRIPTION:
XS GIS Cut Line= 3
      1513869.71      6784530.58      1513660.65      6784573.62
      1513530.23      6784613.05
#Sta/Elev= 30
  4779.9 2188.82  4805.1 2187.47  4825.5 2185.44  4835.8 2184.98  4841.2 2183.95
  4886.4 2180.59  4891.5 2180.52  4927.6 2175.88  4936.7 2173.91  4948.1 2169.75
  4978.7 2161.50  4987.0 2159.34  4991.8 2158.95  5000.1 2154.86  5007.3 2153.32
  5007.6 2152.82  5011.7 2152.82  5012.1 2153.32  5020.1 2156.14  5025.6 2159.01
  5041.0 2159.93  5051.5 2162.34  5058.5 2166.46  5063.7 2167.72  5082.8 2176.02
  5091.5 2178.74  5096.7 2176.96  5103.7 2180.56  5114.2 2182.82  5129.6 2183.00
#Mann=4,-1,0
  4779.9    0.16       0  5000.1    0.07       0  5007.3    0.07       0
  5012.1    0.07       0
Bank Sta=5007.3,5012.1
Exp/Cntr=0.3,0.1

Type RM Length L Ch R = 1,74,0,0,0
BEGIN DESCRIPTION:
322
END DESCRIPTION:
XS GIS Cut Line= 3
      1513765.22      6784050.97      1513530.00      6784063.00
      1513530.00      6784312.97
#Sta/Elev= 30
  4790.2 2192.13  4792.8 2192.13  4801.9 2186.86  4810.5 2184.17  4820.5 2186.96
  4827.7 2190.50  4832.7 2186.02  4840.5 2188.95  4850.5 2189.41  4870.5 2185.28
  4890.6 2178.32  4910.6 2174.08  4930.6 2166.66  4940.6 2161.91  4960.6 2157.35
  4969.6 2156.79  4980.7 2156.81  5000.7 2151.47  5010.7 2150.10  5018.3 2145.05
  5018.7 2144.55  5023.1 2145.05  5050.7 2146.81  5070.7 2149.90  5130.7 2153.06
  5150.7 2155.22  5170.7 2155.96  5175.7 2155.19  5270.7 2165.61  5275.7 2168.24
#Mann=5,-1,0
  4790.2    0.07       0  4801.9    0.16       0  4969.6    0.07       0
  5018.3    0.07       0  5023.1    0.07       0
Bank Sta=5018.3,5023.1
Exp/Cntr=0.3,0.1

Chan Stop Cuts=-1