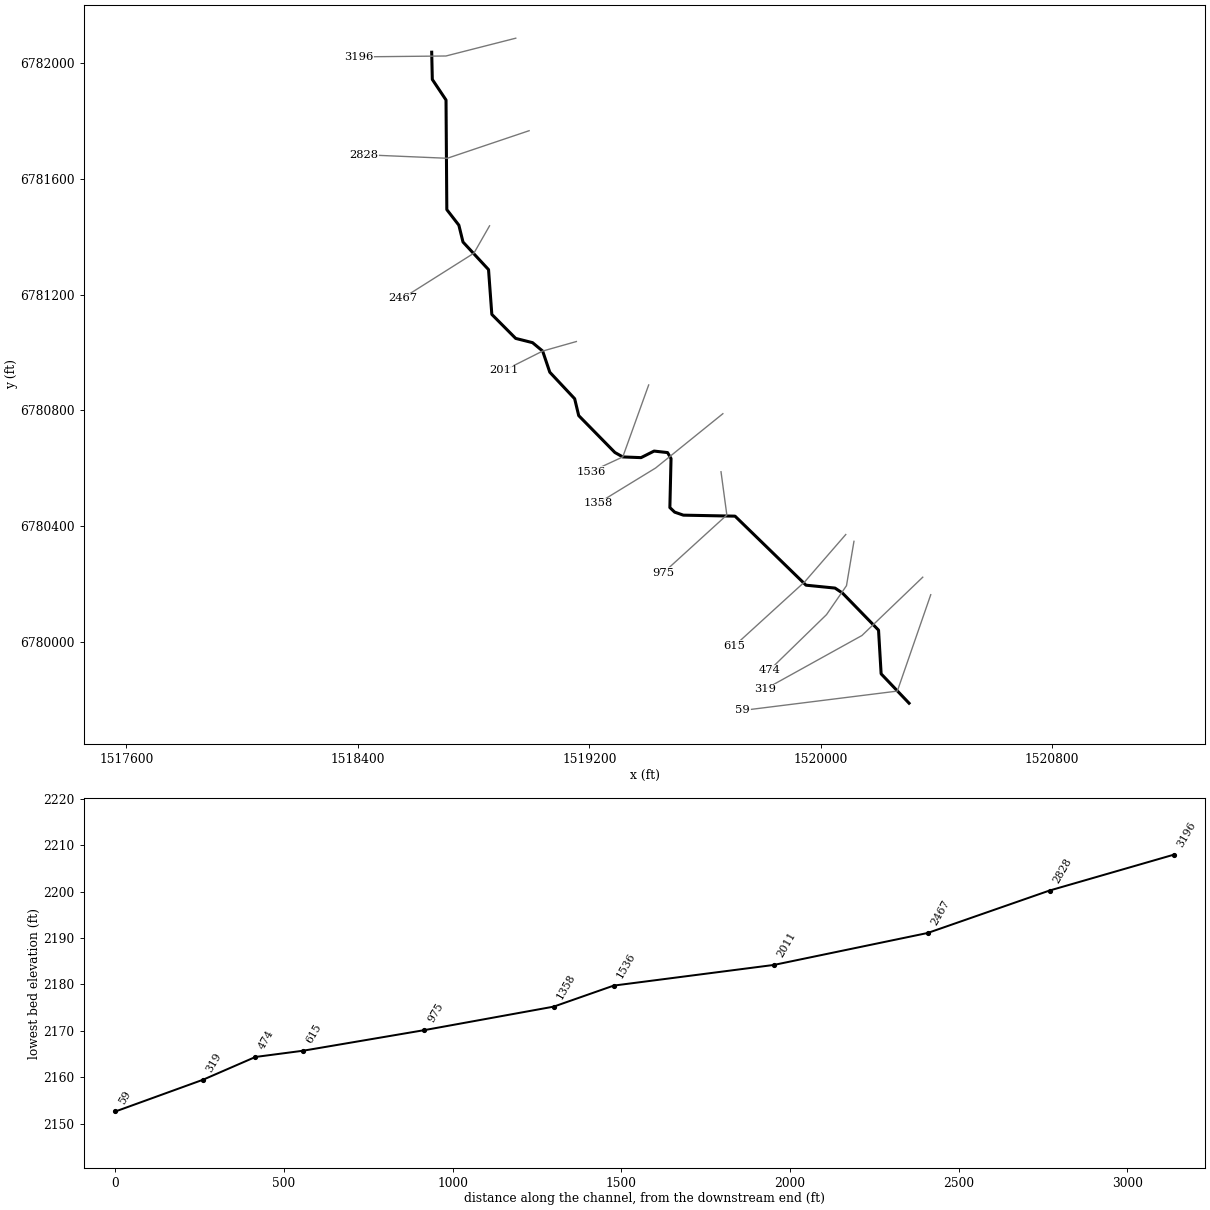
--- Elm 51.prj (project) ---

Proj Title=Elm 51 Base Level Engineering
Current Plan=p01
Default Exp/Contr=0.3,0.1
English Units
Geom File=g01
Flow File=f01
Plan File=p01
BEGIN DESCRIPTION:
Elm 51
END DESCRIPTION:

--- Elm 51.p01 (plan) ---

Plan Title=Multiple Run
Short Identifier=Multiple
Geom File=g01
Flow File=f01
Subcritical Flow
K Sum by GR= 0
Std Step Tol= 0.01
Critical Tol= 0.01
Num of Std Step Trials= 20
Max Error Tol= 0.3
Flow Tol Ratio= 0.001
Split Flow NTrial= 30
Split Flow Tol= 0.02
Split Flow Ratio= 0.02
Log Output Level= 0
Friction Slope Method= 1
Unsteady Friction Slope Method= 2
Unsteady Bridges Friction Slope Method= 1
Parabolic Critical Depth
Global Vel Dist=  1 , 1 , 1
Global Log Level= 0
CheckData=True
Encroach Param= -1, 0, 0, 0
BEGIN DESCRIPTION:
Multiple Run
END DESCRIPTION:

--- Elm 51.f01 (steady flow) ---

Flow Title=Multiple
Number of Profiles=7
Profile Names=10-year,25-year,50-year,1pct_min,100-year,1pct_plu,500-year
River Rch & RM= Elm 51,Reach-1,3196
     184     252     308     235     376     517     566
Boundary for River Rch & Prof#=Elm 51,Reach-1,1
Up Type=0
Dn Type=3
Dn Slope=0.005
Boundary for River Rch & Prof#=Elm 51,Reach-1,2
Up Type=0
Dn Type=3
Dn Slope=0.005
Boundary for River Rch & Prof#=Elm 51,Reach-1,3
Up Type=0
Dn Type=3
Dn Slope=0.005
Boundary for River Rch & Prof#=Elm 51,Reach-1,4
Up Type=0
Dn Type=3
Dn Slope=0.005
Boundary for River Rch & Prof#=Elm 51,Reach-1,5
Up Type=0
Dn Type=3
Dn Slope=0.005
Boundary for River Rch & Prof#=Elm 51,Reach-1,6
Up Type=0
Dn Type=3
Dn Slope=0.005
Boundary for River Rch & Prof#=Elm 51,Reach-1,7
Up Type=0
Dn Type=3
Dn Slope=0.005

--- Elm 51.g01 (geometry) ---

Geom Title=Existing Conditions

River Reach=Elm 51,Reach-1
Reach XY= 30
      1518655.00      6782038.00      1518657.10      6781943.87
      1518704.49      6781872.79      1518707.24      6781493.93
      1518748.86      6781440.17      1518763.16      6781381.95
      1518851.45      6781286.53      1518862.81      6781131.79
      1518945.31      6781048.78      1519003.57      6781034.11
      1519038.50      6781005.05      1519063.18      6780931.98
      1519149.13      6780840.28      1519163.16      6780781.95
      1519288.25      6780654.46      1519315.49      6780639.17
      1519378.59      6780636.73      1519423.67      6780659.37
      1519470.19      6780654.20      1519482.25      6780633.53
      1519478.23      6780464.15      1519494.83      6780448.32
      1519524.87      6780437.91      1519703.54      6780434.46
      1519948.83      6780195.86      1520049.11      6780185.85
      1520075.16      6780168.37      1520199.53      6780040.45
      1520208.49      6779889.45      1520305.00      6779788.00

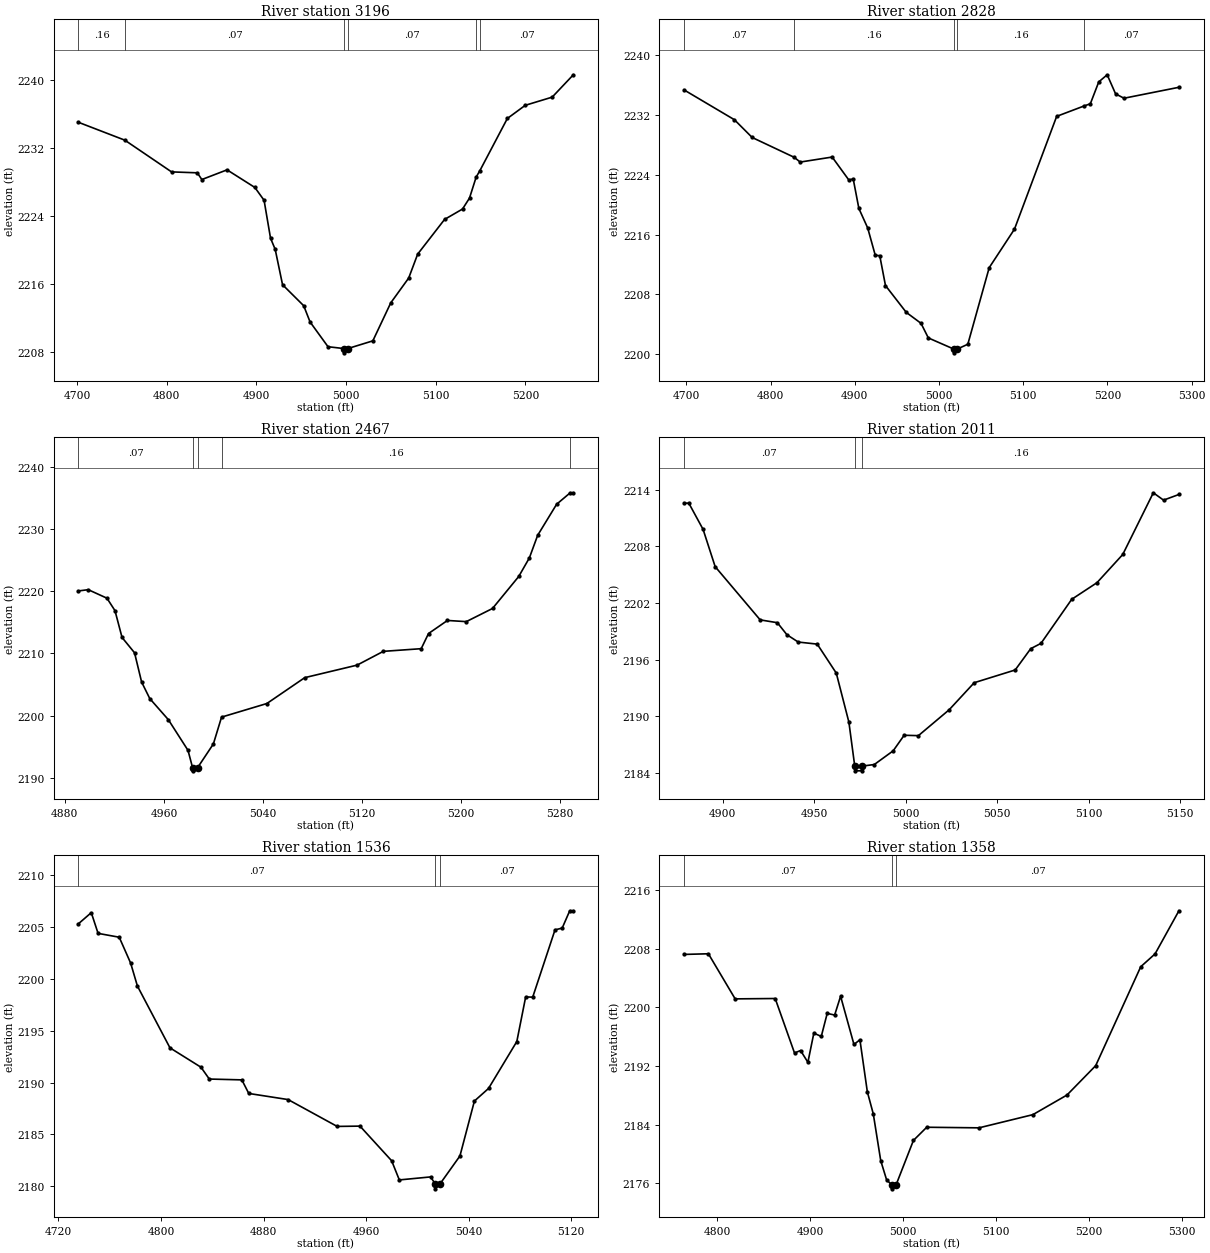
Type RM Length L Ch R = 1,3196,368,368,368
BEGIN DESCRIPTION:
442
END DESCRIPTION:
XS GIS Cut Line= 3
      1518945.56      6782086.43      1518704.19      6782024.91
      1518401.39      6782021.86
#Sta/Elev= 30
  4701.6 2235.03  4753.3 2232.93  4805.4 2229.20  4834.1 2229.09  4839.2 2228.30
  4867.3 2229.44  4898.3 2227.37  4908.6 2225.86  4915.8 2221.40  4921.0 2220.09
  4929.2 2215.93  4952.8 2213.46  4959.9 2211.55  4979.9 2208.64  4997.9 2208.42
  4998.1 2207.92  5001.9 2208.42  5029.9 2209.33  5049.9 2213.80  5069.9 2216.72
  5079.9 2219.53  5109.9 2223.61  5129.9 2224.83  5137.7 2226.12  5145.1 2228.58
  5149.3 2229.35  5179.9 2235.48  5199.9 2237.03  5229.9 2237.99  5253.5 2240.62
#Mann=6,-1,0
  4701.6    0.16       0  4753.3    0.07       0  4997.9    0.07       0
  5001.9    0.07       0  5145.1    0.16       0  5149.3    0.07       0
Bank Sta=4997.9,5001.9
Exp/Cntr=0.3,0.1

Type RM Length L Ch R = 1,2828,361,361,361
BEGIN DESCRIPTION:
789
END DESCRIPTION:
XS GIS Cut Line= 3
      1518991.70      6781766.70      1518708.82      6781671.38
      1518419.89      6781683.68
#Sta/Elev= 30
  4697.2 2235.30  4757.0 2231.32  4778.1 2228.95  4828.1 2226.30  4835.1 2225.67
  4873.1 2226.34  4892.8 2223.29  4898.1 2223.41  4904.8 2219.48  4915.3 2216.87
  4924.3 2213.22  4929.6 2213.18  4936.4 2209.19  4961.1 2205.61  4978.6 2204.15
  4987.3 2202.20  5017.6 2200.71  5017.8 2200.21  5021.6 2200.71  5034.2 2201.36
  5059.6 2211.58  5089.6 2216.72  5139.7 2231.77  5172.1 2233.15  5179.7 2233.45
  5189.7 2236.37  5199.7 2237.32  5209.7 2234.77  5219.7 2234.19  5284.9 2235.65
#Mann=5,-1,0
  4697.2    0.07       0  4828.1    0.16       0  5017.6    0.07       0
  5021.6    0.16       0  5172.1    0.07       0
Bank Sta=5017.6,5021.6
Exp/Cntr=0.3,0.1

Type RM Length L Ch R = 1,2467,456,456,456
BEGIN DESCRIPTION:
441
END DESCRIPTION:
XS GIS Cut Line= 3
      1518854.98      6781437.96      1518800.85      6781343.35
      1518555.01      6781188.01
#Sta/Elev= 30
  4891.0 2220.08  4898.9 2220.28  4914.0 2218.91  4920.5 2216.90  4926.2 2212.58
  4936.3 2210.11  4942.0 2205.40  4948.6 2202.73  4963.6 2199.33  4979.5 2194.38
  4983.2 2191.58  4983.5 2191.08  4987.2 2191.58  5000.0 2195.42  5006.6 2199.74
  5043.2 2201.93  5073.8 2206.10  5116.1 2208.12  5137.3 2210.34  5167.9 2210.77
  5173.8 2213.21  5189.1 2215.32  5204.3 2215.13  5225.5 2217.25  5246.7 2222.41
  5255.3 2225.41  5262.0 2229.05  5277.3 2234.05  5288.3 2235.90  5290.8 2235.90
#Mann=5,-1,0
  4891.0    0.07       0  4983.2    0.07       0  4987.2    0.07       0
  5006.6    0.16       0  5288.3    0.07       0
Bank Sta=4983.2,4987.2
Exp/Cntr=0.3,0.1

Type RM Length L Ch R = 1,2011,475,475,475
BEGIN DESCRIPTION:
440
END DESCRIPTION:
XS GIS Cut Line= 3
      1519155.03      6781038.01      1519038.50      6781005.05
      1518905.00      6780938.00
#Sta/Elev= 30
  4878.9 2212.57  4881.5 2212.57  4889.3 2209.79  4895.9 2205.84  4920.5 2200.20
  4929.9 2199.90  4935.1 2198.63  4941.3 2197.85  4951.7 2197.63  4962.1 2194.56
  4969.0 2189.36  4972.2 2184.70  4972.5 2184.20  4976.0 2184.20  4976.2 2184.70
  4982.9 2184.87  4993.2 2186.32  4999.2 2187.97  5007.0 2187.93  5023.8 2190.67
  5037.5 2193.54  5059.9 2194.89  5068.4 2197.15  5074.0 2197.71  5090.8 2202.38
  5104.6 2204.14  5118.7 2207.13  5135.4 2213.67  5141.0 2212.89  5149.4 2213.49
#Mann=3,-1,0
  4878.9    0.07       0  4972.2    0.07       0  4976.2    0.16       0
Bank Sta=4972.2,4976.2
Exp/Cntr=0.3,0.1

Type RM Length L Ch R = 1,1536,178,178,178
BEGIN DESCRIPTION:
439
END DESCRIPTION:
XS GIS Cut Line= 3
      1519404.99      6780887.96      1519315.49      6780639.17
      1519204.96      6780587.98
#Sta/Elev= 30
  4735.6 2205.32  4745.6 2206.39  4750.9 2204.39  4767.4 2204.02  4776.3 2201.53
  4781.6 2199.31  4807.0 2193.35  4831.2 2191.48  4837.7 2190.34  4863.1 2190.26
  4868.5 2188.95  4899.2 2188.36  4937.5 2185.77  4955.3 2185.80  4980.0 2182.46
  4986.0 2180.61  5010.4 2180.90  5013.9 2180.25  5014.1 2179.75  5017.9 2180.25
  5033.3 2182.92  5044.6 2188.22  5055.6 2189.43  5077.7 2193.96  5084.6 2198.26
  5090.1 2198.24  5107.5 2204.73  5113.1 2204.90  5119.0 2206.57  5121.8 2206.57
#Mann=3,-1,0
  4735.6    0.07       0  5013.9    0.07       0  5017.9    0.07       0
Bank Sta=5013.9,5017.9
Exp/Cntr=0.3,0.1

Type RM Length L Ch R = 1,1358,383,383,383
BEGIN DESCRIPTION:
858
END DESCRIPTION:
XS GIS Cut Line= 3
      1519661.44      6780788.59      1519428.84      6780600.79
      1519229.47      6780478.76
#Sta/Elev= 30
  4764.4 2207.23  4790.6 2207.32  4819.4 2201.16  4862.5 2201.21  4883.3 2193.77
  4889.8 2194.11  4897.7 2192.50  4904.1 2196.48  4912.1 2196.03  4918.5 2199.18
  4926.5 2198.95  4932.9 2201.52  4947.3 2194.93  4953.7 2195.58  4961.7 2188.46
  4968.1 2185.45  4976.1 2179.07  4982.5 2176.42  4988.5 2175.72  4988.7 2175.22
  4992.5 2175.72  5011.3 2181.83  5025.6 2183.63  5081.9 2183.55  5139.9 2185.35
  5176.6 2188.03  5207.5 2192.04  5256.0 2205.55  5271.4 2207.30  5297.1 2213.19
#Mann=3,-1,0
  4764.4    0.07       0  4988.5    0.07       0  4992.5    0.07       0
Bank Sta=4988.5,4992.5
Exp/Cntr=0.3,0.1

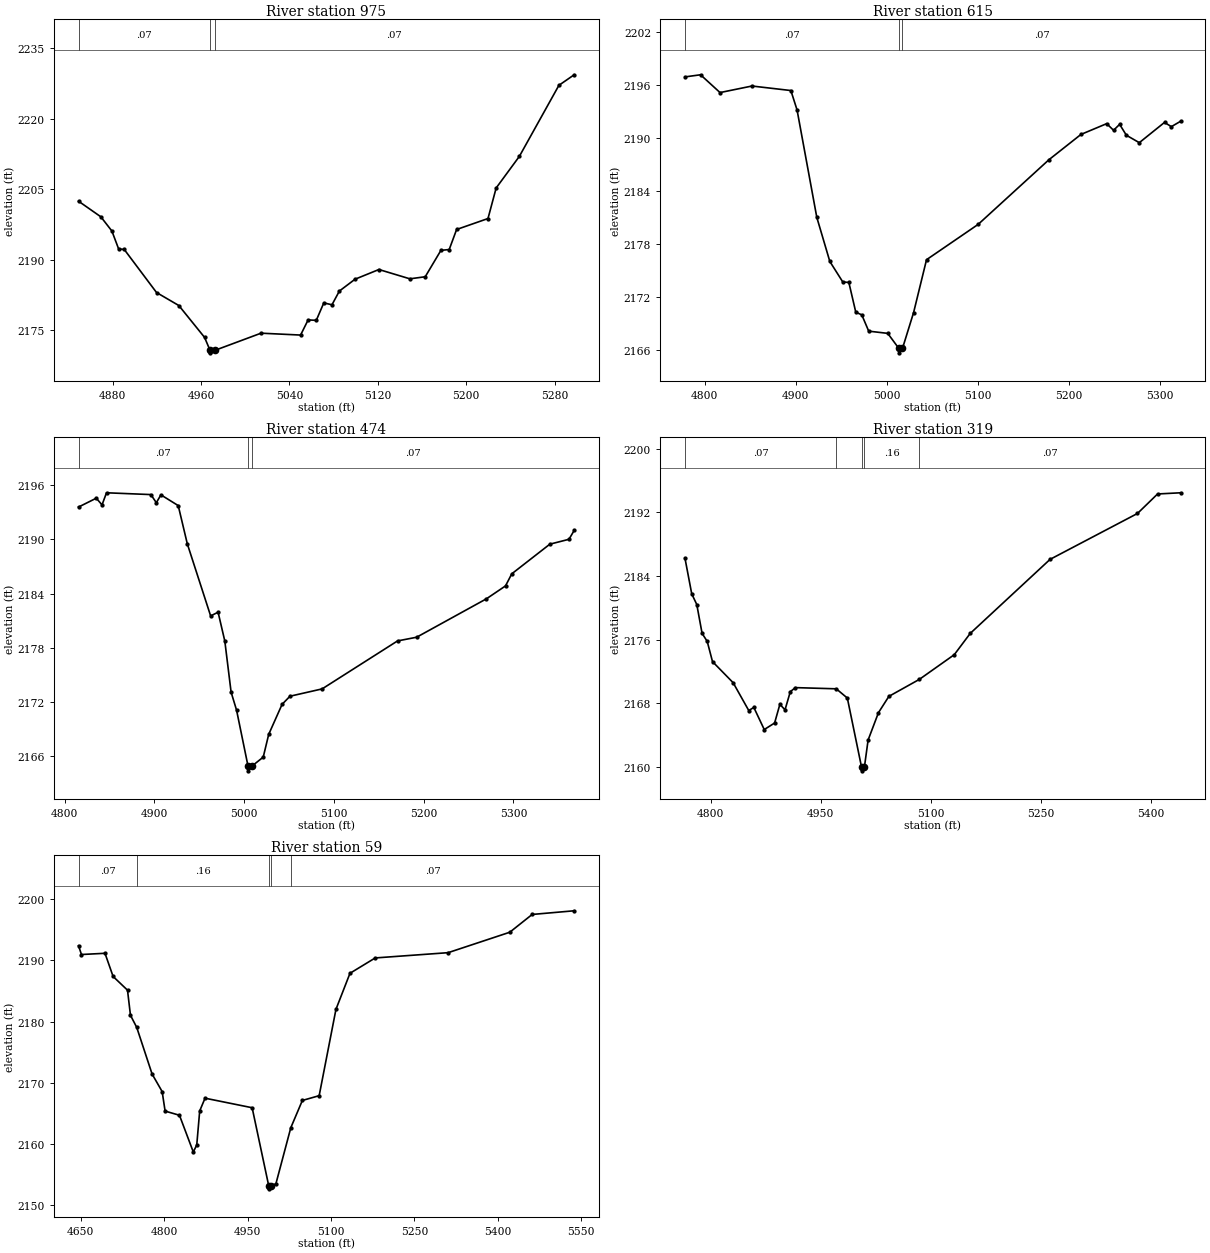
Type RM Length L Ch R = 1,975,360,360,360
BEGIN DESCRIPTION:
438
END DESCRIPTION:
XS GIS Cut Line= 3
      1519655.00      6780587.97      1519675.18      6780438.43
      1519455.03      6780238.03
#Sta/Elev= 30
  4849.1 2202.42  4869.3 2199.10  4879.3 2196.08  4885.4 2192.27  4890.5 2192.15
  4919.7 2183.00  4939.9 2180.23  4963.2 2173.45  4968.2 2170.67  4968.4 2170.17
  4972.2 2170.67  5014.3 2174.35  5050.1 2173.95  5056.9 2177.17  5064.3 2177.08
  5071.1 2180.79  5078.5 2180.39  5085.2 2183.31  5099.4 2185.83  5121.0 2187.89
  5149.0 2185.91  5162.9 2186.35  5177.1 2191.96  5184.6 2192.14  5191.3 2196.40
  5219.7 2198.73  5227.1 2205.23  5248.1 2211.95  5283.9 2227.06  5297.7 2229.30
#Mann=3,-1,0
  4849.1    0.07       0  4968.2    0.07       0  4972.2    0.07       0
Bank Sta=4968.2,4972.2
Exp/Cntr=0.3,0.1

Type RM Length L Ch R = 1,615,141,141,141
BEGIN DESCRIPTION:
788
END DESCRIPTION:
XS GIS Cut Line= 3
      1520086.19      6780370.95      1519944.73      6780207.96
      1519701.87      6779986.62
#Sta/Elev= 30
  4778.5 2196.90  4795.6 2197.14  4817.0 2195.13  4852.1 2195.87  4894.8 2195.36
  4901.6 2193.17  4923.3 2181.03  4937.6 2176.05  4951.8 2173.74  4958.5 2173.68
  4966.1 2170.32  4972.7 2170.02  4980.3 2168.18  5001.2 2167.93  5013.4 2166.23
  5013.6 2165.73  5017.4 2166.23  5029.6 2170.28  5043.8 2176.25  5100.5 2180.24
  5178.2 2187.54  5213.4 2190.40  5241.7 2191.62  5249.2 2190.87  5255.9 2191.54
  5263.3 2190.31  5277.5 2189.47  5305.2 2191.76  5312.7 2191.28  5322.9 2191.89
#Mann=3,-1,0
  4778.5    0.07       0  5013.4    0.07       0  5017.4    0.07       0
Bank Sta=5013.4,5017.4
Exp/Cntr=0.3,0.1

Type RM Length L Ch R = 1,474,155,155,155
BEGIN DESCRIPTION:
857
END DESCRIPTION:
XS GIS Cut Line= 4
      1520114.57      6780347.53      1520088.72      6780194.18
      1520019.80      6780094.25      1519822.58      6779902.17
#Sta/Elev= 30
  4815.5 2193.59  4835.3 2194.57  4841.7 2193.83  4846.7 2195.17  4896.1 2194.97
  4902.2 2194.07  4907.3 2194.94  4926.6 2193.75  4936.7 2189.52  4962.7 2181.54
  4971.0 2181.95  4978.5 2178.75  4985.5 2173.10  4991.6 2171.10  5004.4 2164.89
  5004.7 2164.39  5008.4 2164.89  5021.3 2165.91  5027.4 2168.43  5042.3 2171.75
  5051.1 2172.65  5086.9 2173.46  5170.9 2178.77  5192.2 2179.18  5269.9 2183.43
  5291.2 2184.86  5298.2 2186.20  5340.6 2189.48  5361.9 2190.02  5367.7 2191.00
#Mann=3,-1,0
  4815.5    0.07       0  5004.4    0.07       0  5008.4    0.07       0
Bank Sta=5004.4,5008.4
Exp/Cntr=0.3,0.1

Type RM Length L Ch R = 1,319,260,260,260
BEGIN DESCRIPTION:
856
END DESCRIPTION:
XS GIS Cut Line= 3
      1520352.34      6780223.48      1520142.13      6780021.89
      1519806.17      6779835.81
#Sta/Elev= 30
  4765.0 2186.22  4774.2 2181.75  4781.1 2180.40  4788.3 2176.78  4795.3 2175.77
  4802.5 2173.23  4830.6 2170.58  4851.9 2167.08  4858.8 2167.47  4873.0 2164.69
  4887.1 2165.51  4894.3 2167.86  4901.3 2167.17  4908.5 2169.45  4915.4 2169.96
  4971.1 2169.81  4986.2 2168.65  5005.5 2160.00  5005.8 2159.50  5009.5 2160.00
  5014.5 2163.37  5028.6 2166.81  5042.8 2168.86  5084.4 2171.00  5131.9 2174.10
  5153.6 2176.77  5262.4 2186.08  5381.5 2191.85  5408.9 2194.30  5440.3 2194.45
#Mann=5,-1,0
  4765.0    0.07       0  4971.1    0.16       0  5005.5    0.07       0
  5009.5    0.16       0  5084.4    0.07       0
Bank Sta=5005.5,5009.5
Exp/Cntr=0.3,0.1

Type RM Length L Ch R = 1,59,0,0,0
BEGIN DESCRIPTION:
437
END DESCRIPTION:
XS GIS Cut Line= 3
      1520379.99      6780162.97      1520264.47      6779829.81
      1519730.05      6779763.01
#Sta/Elev= 30
  4645.9 2192.41  4651.2 2190.97  4693.5 2191.17  4708.1 2187.38  4734.0 2185.14
  4739.3 2181.04  4750.6 2179.05  4778.2 2171.43  4796.3 2168.56  4801.6 2165.37
  4827.4 2164.69  4852.3 2158.68  4858.5 2159.83  4863.8 2165.40  4873.4 2167.48
  4958.1 2165.92  4987.9 2153.16  4988.1 2152.66  4991.9 2153.16  5000.8 2153.48
  5027.6 2162.65  5048.4 2167.11  5078.6 2167.89  5108.8 2182.01  5134.0 2187.90
  5179.4 2190.41  5310.4 2191.27  5421.3 2194.61  5461.6 2197.52  5537.1 2198.12
#Mann=5,-1,0
  4645.9    0.07       0  4750.6    0.16       0  4987.9    0.07       0
  4991.9    0.16       0  5027.6    0.07       0
Bank Sta=4987.9,4991.9
Exp/Cntr=0.3,0.1

Chan Stop Cuts=-1