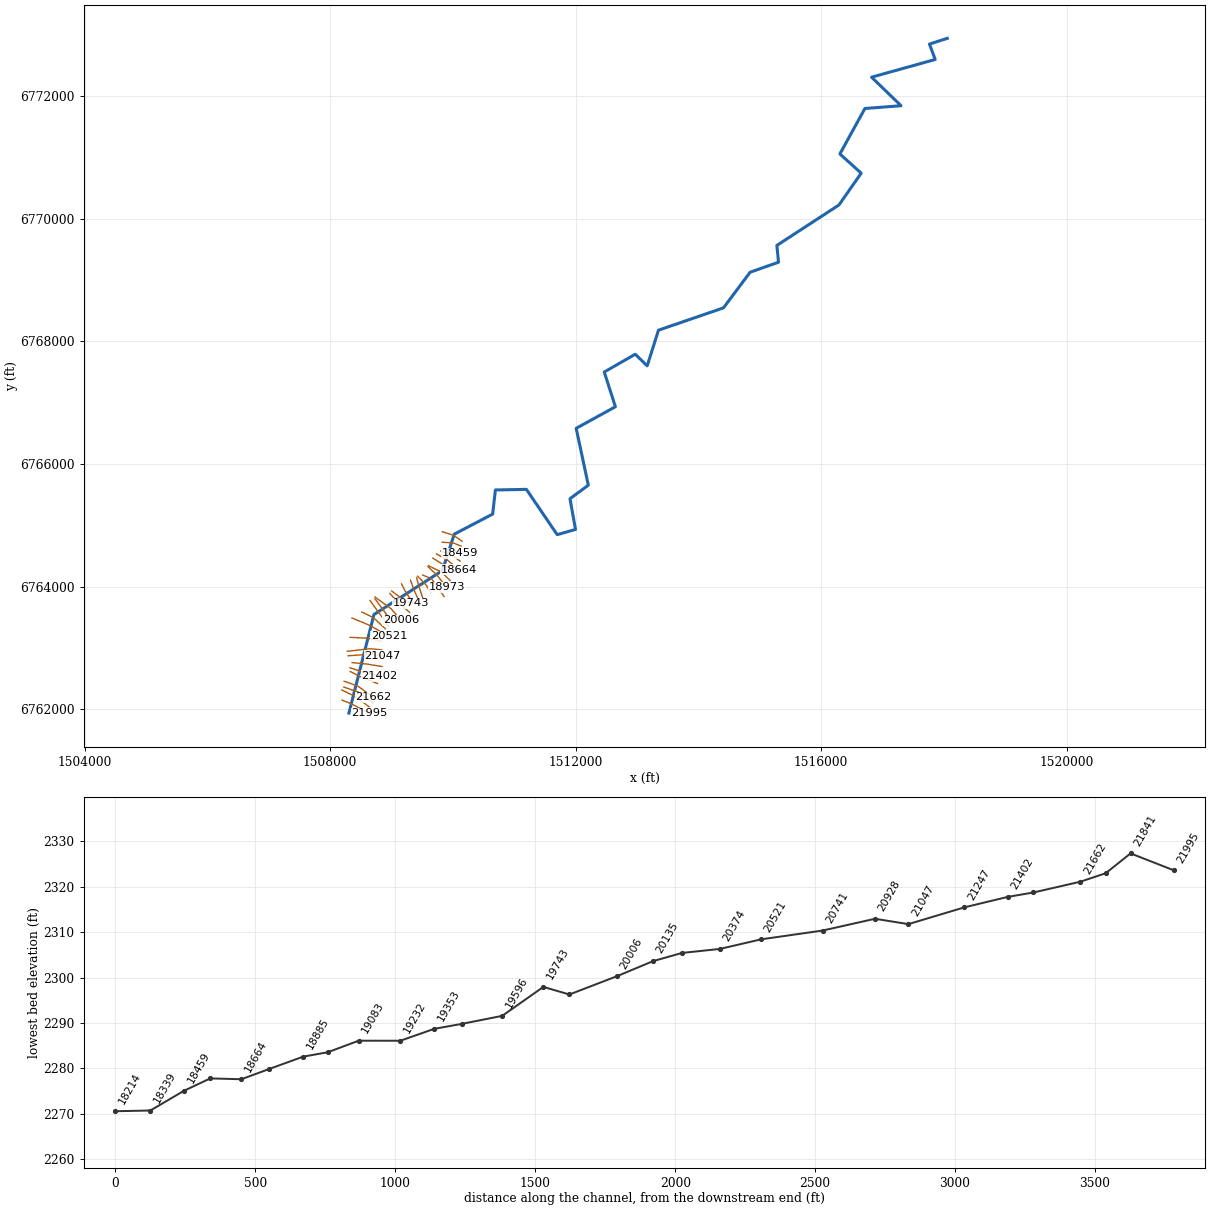
--- Elm 52.prj (project) ---

Proj Title=Elm 52 Base Level Engineering
Current Plan=p01
Default Exp/Contr=0.3,0.1
English Units
Geom File=g01
Flow File=f01
Plan File=p01
BEGIN DESCRIPTION:
Elm 52
END DESCRIPTION:

--- Elm 52.p01 (plan) ---

Plan Title=Multiple Run
Short Identifier=Multiple
Geom File=g01
Flow File=f01
Subcritical Flow
K Sum by GR= 0
Std Step Tol= 0.01
Critical Tol= 0.01
Num of Std Step Trials= 20
Max Error Tol= 0.3
Flow Tol Ratio= 0.001
Split Flow NTrial= 30
Split Flow Tol= 0.02
Split Flow Ratio= 0.02
Log Output Level= 0
Friction Slope Method= 1
Unsteady Friction Slope Method= 2
Unsteady Bridges Friction Slope Method= 1
Parabolic Critical Depth
Global Vel Dist=  1 , 1 , 1
Global Log Level= 0
CheckData=True
Encroach Param= -1, 0, 0, 0
BEGIN DESCRIPTION:
Multiple Run
END DESCRIPTION:

--- Elm 52.f01 (steady flow) ---

Flow Title=Multiple
Number of Profiles=7
Profile Names=10-year,25-year,50-year,1pct_min,100-year,1pct_plu,500-year
River Rch & RM= Elm 52,Reach-1,21995
     232     323     400     307     492     677     755
River Rch & RM= Elm 52,Reach-1,19836
     344     491     616     480     769    1060    1210
River Rch & RM= Elm 52,Reach-1,15251
     561     820    1050     826    1320    1820    2150
River Rch & RM= Elm 52,Reach-1,7211
     662     974    1250     991    1590    2190    2600
River Rch & RM= Elm 52,Reach-1,4534
     735    1090    1400    1110    1780    2450    2930
Boundary for River Rch & Prof#=Elm 52,Reach-1,1
Up Type=0
Dn Type=3
Dn Slope=0.005
Boundary for River Rch & Prof#=Elm 52,Reach-1,2
Up Type=0
Dn Type=3
Dn Slope=0.005
Boundary for River Rch & Prof#=Elm 52,Reach-1,3
Up Type=0
Dn Type=3
Dn Slope=0.005
Boundary for River Rch & Prof#=Elm 52,Reach-1,4
Up Type=0
Dn Type=3
Dn Slope=0.005
Boundary for River Rch & Prof#=Elm 52,Reach-1,5
Up Type=0
Dn Type=3
Dn Slope=0.005
Boundary for River Rch & Prof#=Elm 52,Reach-1,6
Up Type=0
Dn Type=3
Dn Slope=0.005
Boundary for River Rch & Prof#=Elm 52,Reach-1,7
Up Type=0
Dn Type=3
Dn Slope=0.005

--- Elm 52.g01 (geometry) ---

Geom Title=Existing Conditions

River Reach=Elm 52,Reach-1
Reach XY= 30
      1508305.00      6761938.00      1508713.00      6763544.39
      1509828.73      6764261.12      1510021.43      6764854.77
      1510647.20      6765181.79      1510691.36      6765574.56
      1511196.69      6765584.92      1511698.33      6764846.77
      1511997.38      6764931.50      1511906.88      6765432.31
      1512205.67      6765653.07      1512007.82      6766580.05
      1512647.20      6766931.79      1512465.02      6767498.05
      1512970.23      6767787.76      1513164.86      6767598.89
      1513348.83      6768180.14      1514407.43      6768543.52
      1514841.76      6769124.89      1515305.00      6769288.00
      1515277.70      6769561.90      1516288.73      6770220.79
      1516651.69      6770739.80      1516304.55      6771053.19
      1516712.67      6771794.52      1517301.48      6771839.45
      1516821.15      6772304.58      1517857.78      6772593.36
      1517763.95      6772844.67      1518055.00      6772938.00

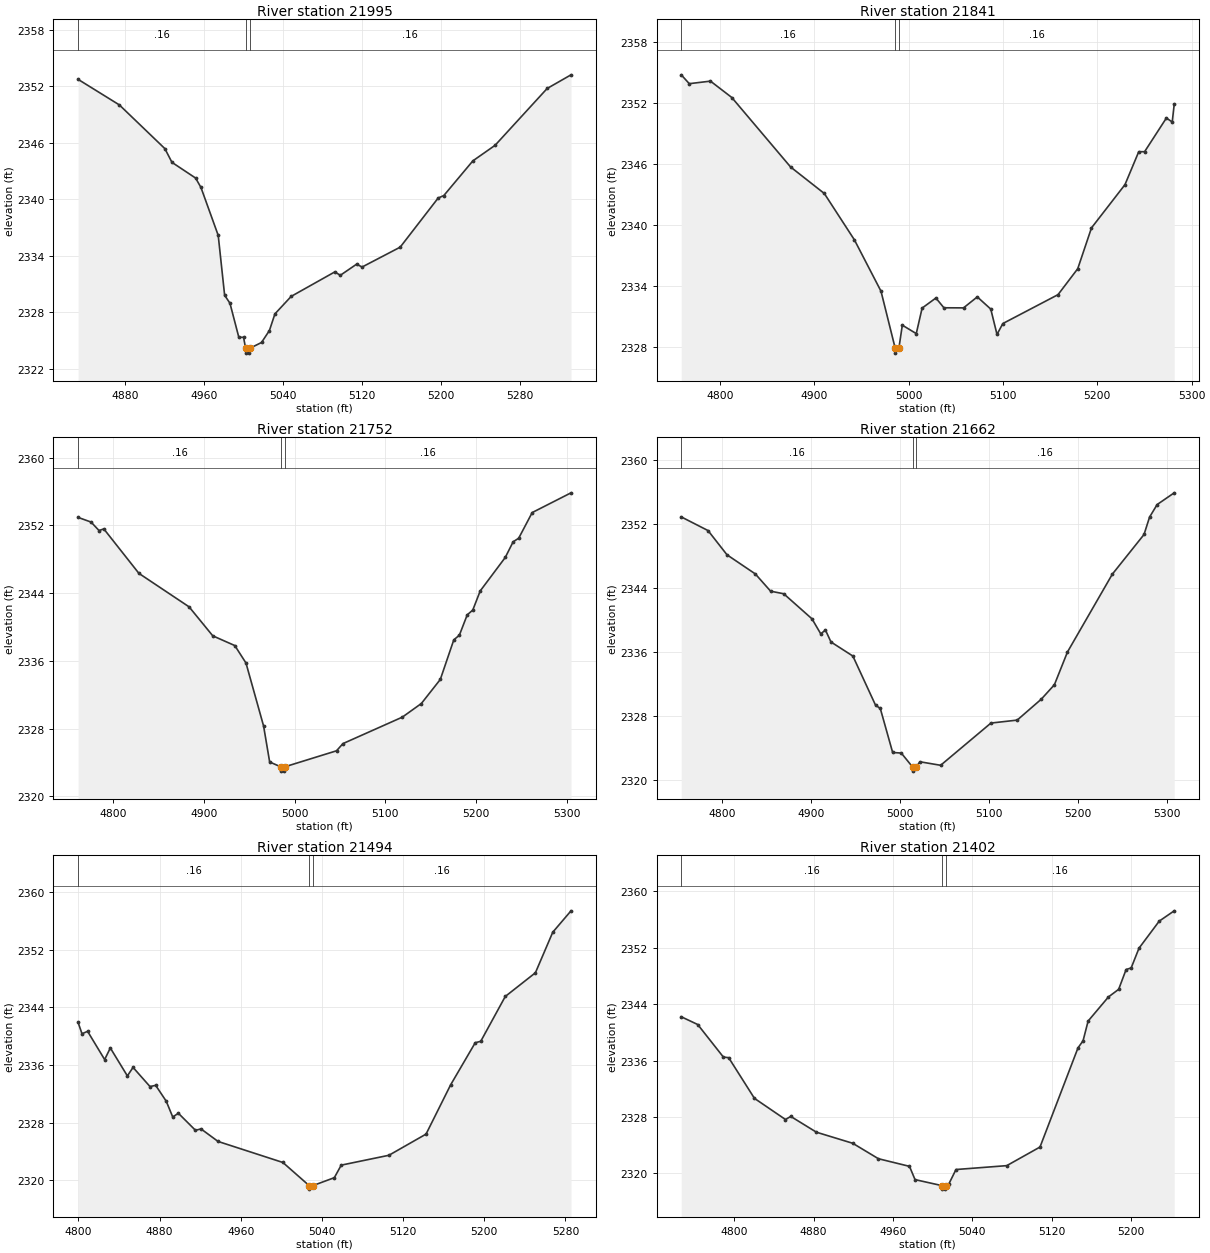
Type RM Length L Ch R = 1,21995,154,154,154
BEGIN DESCRIPTION:
Elm 52 21995.025
END DESCRIPTION:
XS GIS Cut Line= 3
      1508193.58      6762149.84      1508348.81      6762086.13
      1508643.29      6761932.81
#Sta/Elev= 30
  4832.2 2352.74  4874.1 2350.02  4920.2 2345.38  4927.4 2343.92  4951.4 2342.25
  4956.8 2341.25  4974.3 2336.16  4980.8 2329.80  4986.2 2328.95  4995.2 2325.33
  5000.0 2325.33  5002.1 2324.15  5002.3 2323.65  5005.8 2323.65  5006.1 2324.15
  5018.2 2324.78  5026.2 2326.05  5031.8 2327.82  5048.3 2329.68  5092.5 2332.28
  5098.1 2331.92  5114.6 2333.10  5120.2 2332.80  5158.8 2334.91  5197.3 2340.13
  5203.0 2340.39  5232.5 2344.08  5255.0 2345.73  5307.8 2351.77  5332.0 2353.22
#Mann=3,-1,0
  4832.2    0.16       0  5002.1    0.07       0  5006.1    0.16       0
Bank Sta=5002.1,5006.1
Exp/Cntr=0.3,0.1

Type RM Length L Ch R = 1,21841,89,89,89
BEGIN DESCRIPTION:
Elm 52 21841.21
END DESCRIPTION:
XS GIS Cut Line= 3
      1508188.41      6762314.76      1508400.22      6762212.33
      1508631.40      6762041.53
#Sta/Elev= 30
  4758.8 2354.73  4767.3 2353.86  4789.8 2354.11  4812.4 2352.50  4874.7 2345.67
  4910.5 2343.06  4942.4 2338.50  4970.6 2333.45  4985.6 2327.86  4985.9 2327.36
  4989.6 2327.86  4993.2 2330.11  5008.0 2329.28  5014.2 2331.79  5028.8 2332.78
  5037.3 2331.82  5058.1 2331.81  5072.7 2332.89  5087.0 2331.69  5093.6 2329.20
  5099.8 2330.27  5158.3 2333.11  5179.2 2335.66  5193.8 2339.68  5229.3 2343.93
  5243.9 2347.17  5250.1 2347.17  5273.2 2350.48  5279.4 2350.09  5281.5 2351.83
#Mann=3,-1,0
  4758.8    0.16       0  4985.6    0.07       0  4989.6    0.16       0
Bank Sta=4985.6,4989.6
Exp/Cntr=0.3,0.1

Type RM Length L Ch R = 1,21752,90,90,90
BEGIN DESCRIPTION:
Elm 52 21752.1
END DESCRIPTION:
XS GIS Cut Line= 3
      1508221.45      6762361.62      1508445.36      6762285.24
      1508697.12      6762109.88
#Sta/Elev= 30
  4761.2 2352.94  4775.5 2352.39  4784.3 2351.39  4789.6 2351.58  4828.3 2346.33
  4883.6 2342.38  4909.7 2338.96  4934.0 2337.81  4946.3 2335.75  4965.7 2328.32
  4972.4 2324.07  4984.8 2323.49  4985.1 2322.99  4988.6 2322.99  4988.8 2323.49
  5046.1 2325.39  5053.2 2326.24  5118.6 2329.36  5139.6 2330.97  5160.5 2333.81
  5175.4 2338.49  5181.5 2339.03  5190.2 2341.44  5196.3 2342.00  5204.5 2344.26
  5232.1 2348.21  5240.8 2350.06  5246.9 2350.48  5261.8 2353.51  5304.6 2355.84
#Mann=3,-1,0
  4761.2    0.16       0  4984.8    0.07       0  4988.8    0.16       0
Bank Sta=4984.8,4988.8
Exp/Cntr=0.3,0.1

Type RM Length L Ch R = 1,21662,168,168,168
BEGIN DESCRIPTION:
Elm 52 21661.81
END DESCRIPTION:
XS GIS Cut Line= 3
      1508226.62      6762457.11      1508450.57      6762377.26
      1508707.50      6762193.23
#Sta/Elev= 30
  4754.5 2352.92  4784.6 2351.21  4805.9 2348.18  4837.7 2345.79  4854.9 2343.63
  4869.6 2343.31  4901.4 2340.17  4911.2 2338.30  4916.5 2338.77  4922.7 2337.28
  4947.3 2335.52  4972.8 2329.37  4978.1 2328.97  4992.0 2323.46  5001.7 2323.39
  5014.5 2321.63  5014.7 2321.13  5018.5 2321.63  5022.6 2322.30  5045.9 2321.86
  5102.4 2327.14  5131.9 2327.51  5159.0 2330.13  5173.7 2331.93  5188.4 2336.03
  5238.8 2345.76  5274.4 2350.72  5280.6 2352.89  5289.1 2354.46  5308.3 2355.93
#Mann=3,-1,0
  4754.5    0.16       0  5014.5    0.07       0  5018.5    0.16       0
Bank Sta=5014.5,5018.5
Exp/Cntr=0.3,0.1

Type RM Length L Ch R = 1,21494,92,92,92
BEGIN DESCRIPTION:
Elm 52 21493.5
END DESCRIPTION:
XS GIS Cut Line= 3
      1508327.31      6762615.10      1508507.86      6762524.83
      1508771.70      6762419.63
#Sta/Elev= 30
  4799.6 2341.90  4803.5 2340.32  4809.0 2340.66  4825.8 2336.74  4831.4 2338.35
  4848.2 2334.47  4853.8 2335.65  4870.5 2332.99  4876.1 2333.16  4886.5 2330.96
  4892.9 2328.77  4898.5 2329.28  4915.3 2326.92  4920.8 2327.11  4937.6 2325.37
  5001.5 2322.45  5027.3 2319.25  5027.6 2318.75  5031.3 2319.25  5052.2 2320.34
  5059.0 2322.08  5106.0 2323.45  5142.6 2326.39  5166.8 2333.22  5191.1 2339.08
  5196.5 2339.27  5220.7 2345.50  5250.4 2348.79  5267.5 2354.42  5285.5 2357.39
#Mann=3,-1,0
  4799.6    0.16       0  5027.3    0.07       0  5031.3    0.16       0
Bank Sta=5027.3,5031.3
Exp/Cntr=0.3,0.1

Type RM Length L Ch R = 1,21402,155,155,155
BEGIN DESCRIPTION:
Elm 52 21402.02
END DESCRIPTION:
XS GIS Cut Line= 3
      1508322.07      6762677.61      1508554.73      6762597.74
      1508799.69      6762542.93
#Sta/Elev= 30
  4746.5 2342.22  4763.1 2341.12  4789.0 2336.50  4794.3 2336.42  4820.3 2330.65
  4851.6 2327.65  4856.9 2328.09  4882.8 2325.85  4919.4 2324.28  4945.3 2322.09
  4976.6 2321.01  4982.2 2319.13  5009.2 2318.28  5009.4 2317.78  5012.9 2317.78
  5013.2 2318.28  5016.3 2318.52  5023.5 2320.56  5074.7 2321.11  5108.2 2323.75
  5146.5 2337.81  5151.6 2338.81  5156.7 2341.61  5177.2 2345.03  5187.5 2346.11
  5195.0 2348.92  5200.1 2349.14  5208.0 2351.94  5228.4 2355.78  5243.5 2357.24
#Mann=3,-1,0
  4746.5    0.16       0  5009.2    0.07       0  5013.2    0.16       0
Bank Sta=5009.2,5013.2
Exp/Cntr=0.3,0.1

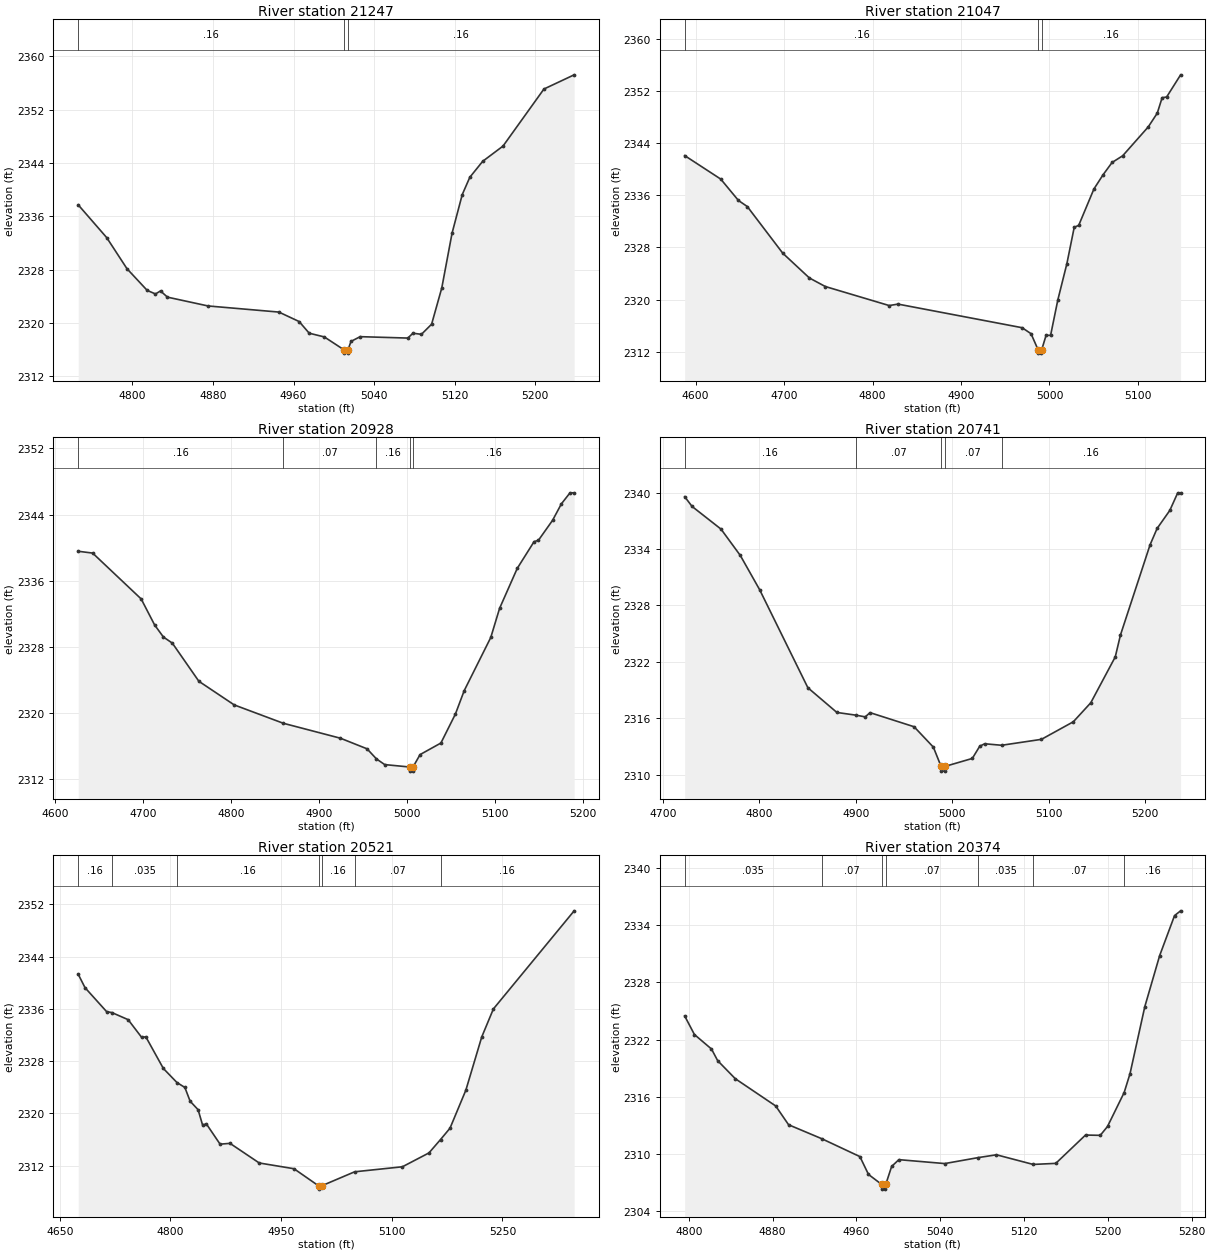
Type RM Length L Ch R = 1,21247,200,200,200
BEGIN DESCRIPTION:
Elm 52 21246.98
END DESCRIPTION:
XS GIS Cut Line= 3
      1508356.80      6762760.94      1508599.87      6762736.63
      1508844.65      6762696.70
#Sta/Elev= 30
  4746.2 2337.72  4774.5 2332.80  4794.6 2328.14  4814.7 2324.88  4822.9 2324.35
  4827.9 2324.80  4834.8 2323.87  4875.0 2322.55  4945.4 2321.63  4965.5 2320.21
  4975.5 2318.46  4990.5 2317.90  5010.0 2315.97  5010.2 2315.47  5013.7 2315.47
  5014.0 2315.97  5017.0 2317.23  5026.1 2317.94  5073.4 2317.73  5078.5 2318.46
  5086.9 2318.29  5097.0 2319.81  5107.1 2325.25  5117.3 2333.47  5127.4 2339.25
  5134.9 2341.85  5147.7 2344.25  5167.9 2346.54  5208.5 2355.10  5238.5 2357.23
#Mann=3,-1,0
  4746.2    0.16       0  5010.0    0.07       0  5014.0    0.16       0
Bank Sta=5010,5014
Exp/Cntr=0.3,0.1

Type RM Length L Ch R = 1,21047,119,119,119
BEGIN DESCRIPTION:
Elm 52 21046.52
END DESCRIPTION:
XS GIS Cut Line= 3
      1508294.33      6762872.05      1508704.04      6762899.83
      1508850.83      6762868.74
#Sta/Elev= 30
  4587.6 2342.09  4628.4 2338.48  4648.4 2335.20  4658.4 2334.27  4698.5 2327.11
  4728.6 2323.31  4746.6 2322.00  4818.8 2319.08  4828.8 2319.30  4969.1 2315.68
  4979.2 2314.76  4987.2 2312.28  4987.4 2311.78  4990.9 2311.78  4991.2 2312.28
  4996.2 2314.51  5001.3 2314.51  5009.5 2319.96  5019.7 2325.50  5028.0 2331.08
  5033.1 2331.39  5050.3 2336.97  5060.6 2339.14  5070.8 2341.03  5082.8 2342.06
  5111.7 2346.49  5121.9 2348.60  5127.4 2350.97  5132.5 2351.08  5148.3 2354.48
#Mann=3,-1,0
  4587.6    0.16       0  4987.2    0.07       0  4991.2    0.16       0
Bank Sta=4987.2,4991.2
Exp/Cntr=0.3,0.1

Type RM Length L Ch R = 1,20928,187,187,187
BEGIN DESCRIPTION:
Elm 52 20928.46
END DESCRIPTION:
XS GIS Cut Line= 3
      1508278.68      6762944.96      1508646.75      6762986.63
      1508839.45      6762969.27
#Sta/Elev= 30
  4626.6 2339.56  4643.0 2339.34  4698.2 2333.79  4713.5 2330.64  4723.5 2329.18
  4733.6 2328.45  4763.8 2323.83  4804.0 2320.97  4859.8 2318.75  4924.8 2316.94
  4955.0 2315.66  4965.7 2314.44  4975.1 2313.75  5003.3 2313.46  5003.6 2312.96
  5007.1 2312.96  5007.3 2313.46  5015.3 2314.96  5039.0 2316.36  5055.5 2319.87
  5065.5 2322.70  5095.7 2329.13  5105.7 2332.65  5125.8 2337.49  5144.9 2340.72
  5149.9 2340.89  5166.0 2343.31  5176.0 2345.30  5185.8 2346.63  5190.5 2346.63
#Mann=5,-1,0
  4626.6    0.16       0  4859.8    0.07       0  4965.7    0.16       0
  5003.3    0.07       0  5007.3    0.16       0
Bank Sta=5003.3,5007.3
Exp/Cntr=0.3,0.1

Type RM Length L Ch R = 1,20741,220,220,220
BEGIN DESCRIPTION:
Elm 52 20741.35
END DESCRIPTION:
XS GIS Cut Line= 3
      1508327.32      6763172.39      1508610.29      6763158.51
      1508835.93      6763108.17
#Sta/Elev= 30
  4722.4 2339.56  4730.1 2338.52  4760.1 2336.11  4780.1 2333.31  4800.2 2329.66
  4850.2 2319.24  4880.3 2316.61  4900.2 2316.32  4909.7 2316.14  4914.7 2316.59
  4960.4 2315.09  4980.4 2312.92  4988.4 2310.87  4988.7 2310.37  4992.2 2310.37
  4992.4 2310.87  5020.8 2311.72  5028.5 2313.02  5033.6 2313.28  5051.2 2313.12
  5092.5 2313.75  5125.6 2315.62  5143.7 2317.64  5169.1 2322.52  5174.5 2324.85
  5205.2 2334.44  5212.5 2336.18  5225.7 2338.10  5233.9 2339.97  5236.9 2339.97
#Mann=5,-1,0
  4722.4    0.16       0  4900.2    0.07       0  4988.4    0.07       0
  4992.4    0.07       0  5051.2    0.16       0
Bank Sta=4988.4,4992.4
Exp/Cntr=0.3,0.1

Type RM Length L Ch R = 1,20521,147,147,147
BEGIN DESCRIPTION:
Elm 52 20521.471
END DESCRIPTION:
XS GIS Cut Line= 3
      1508354.99      6763488.01      1508654.99      6763363.01
      1508954.98      6763188.01
#Sta/Elev= 30
  4675.0 2341.30  4684.2 2339.25  4713.5 2335.58  4720.8 2335.43  4742.7 2334.35
  4761.1 2331.63  4766.6 2331.74  4790.4 2326.89  4808.8 2324.74  4819.6 2323.98
  4826.7 2321.88  4837.5 2320.58  4843.5 2318.27  4848.9 2318.38  4867.3 2315.31
  4880.8 2315.43  4920.4 2312.43  4967.5 2311.55  5000.9 2308.93  5001.2 2308.43
  5004.9 2308.93  5049.7 2311.08  5114.5 2311.85  5150.5 2313.97  5166.2 2316.02
  5179.0 2317.75  5200.5 2323.57  5222.0 2331.70  5237.8 2335.99  5347.3 2351.00
#Mann=7,-1,0
  4675.0    0.16       0  4720.8   0.035       0  4808.8    0.16       0
  5000.9    0.07       0  5004.9    0.16       0  5049.7    0.07       0
  5166.2    0.16       0
Bank Sta=5000.9,5004.9
Exp/Cntr=0.3,0.1

Type RM Length L Ch R = 1,20374,136,136,136
BEGIN DESCRIPTION:
Elm 52 20373.7
END DESCRIPTION:
XS GIS Cut Line= 3
      1508516.58      6763583.83      1508702.30      6763495.31
      1508897.59      6763312.12
#Sta/Elev= 30
  4796.0 2324.48  4805.3 2322.53  4821.6 2321.01  4827.5 2319.79  4844.3 2317.90
  4882.9 2315.04  4895.2 2313.07  4926.8 2311.61  4963.3 2309.73  4971.5 2307.86
  4984.0 2306.82  4984.2 2306.32  4987.7 2306.32  4988.0 2306.82  4993.6 2308.70
  5000.5 2309.41  5044.3 2309.00  5076.5 2309.63  5093.7 2309.92  5128.7 2308.91
  5150.3 2309.02  5178.7 2311.99  5192.8 2311.96  5199.7 2312.89  5215.6 2316.45
  5221.2 2318.43  5235.3 2325.45  5249.5 2330.81  5263.7 2335.00  5269.5 2335.50
#Mann=7,-1,0
  4796.0   0.035       0  4926.8    0.07       0  4984.0    0.07       0
  4988.0    0.07       0  5076.5   0.035       0  5128.7    0.07       0
  5215.6    0.16       0
Bank Sta=4984,4988
Exp/Cntr=0.3,0.1

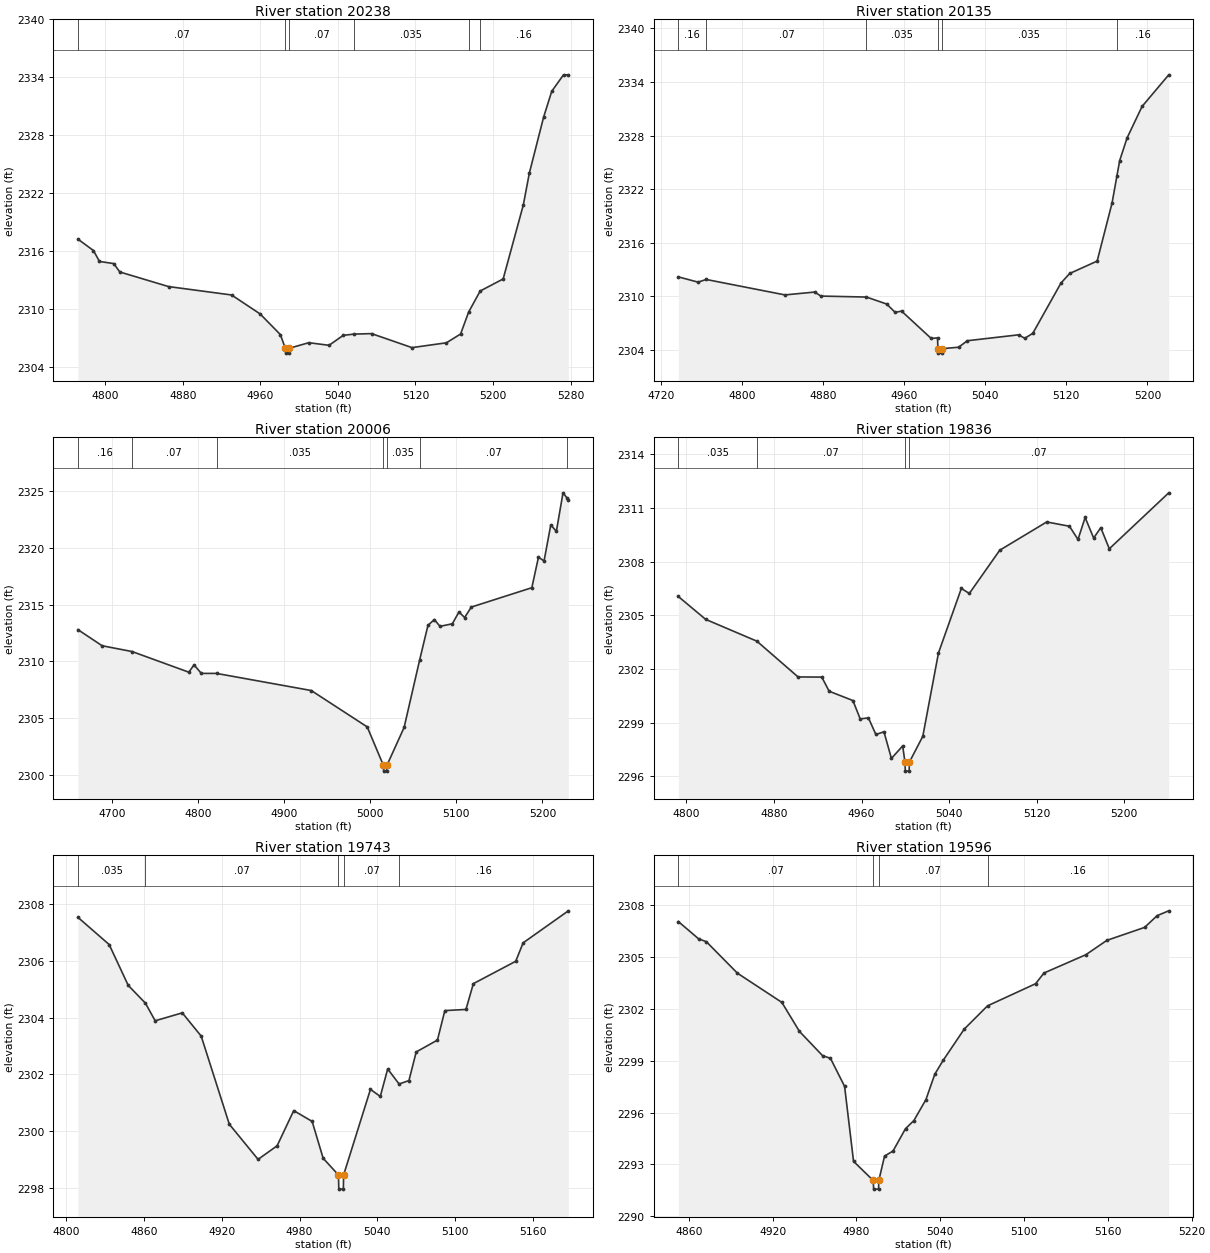
Type RM Length L Ch R = 1,20238,103,103,103
BEGIN DESCRIPTION:
Elm 52 20238.27
END DESCRIPTION:
XS GIS Cut Line= 3
      1508648.50      6763773.06      1508778.69      6763592.53
      1508947.12      6763365.07
#Sta/Elev= 30
  4772.0 2317.23  4788.0 2316.05  4794.2 2314.92  4808.9 2314.70  4815.2 2313.83
  4865.4 2312.32  4930.4 2311.45  4959.8 2309.49  4980.7 2307.35  4985.8 2305.93
  4986.1 2305.43  4989.6 2305.43  4989.8 2305.93  5010.0 2306.51  5030.9 2306.24
  5045.5 2307.27  5056.6 2307.40  5074.7 2307.45  5116.4 2306.00  5151.9 2306.50
  5166.5 2307.41  5174.8 2309.68  5186.7 2311.86  5210.4 2313.11  5231.2 2320.78
  5237.4 2324.07  5252.1 2329.86  5260.5 2332.54  5272.6 2334.24  5277.6 2334.24
#Mann=6,-1,0
  4772.0    0.07       0  4985.8    0.07       0  4989.8    0.07       0
  5056.6   0.035       0  5174.8    0.07       0  5186.7    0.16       0
Bank Sta=4985.8,4989.8
Exp/Cntr=0.3,0.1

Type RM Length L Ch R = 1,20135,129,129,129
BEGIN DESCRIPTION:
Elm 52 20134.76
END DESCRIPTION:
XS GIS Cut Line= 3
      1508730.06      6763800.89      1508882.86      6763592.53
      1509013.06      6763408.52
#Sta/Elev= 30
  4737.2 2312.17  4756.7 2311.58  4764.7 2311.88  4842.4 2310.15  4871.7 2310.47
  4877.9 2310.02  4922.8 2309.91  4942.7 2309.13  4951.2 2308.19  4957.4 2308.34
  4986.7 2305.27  4992.9 2305.34  4993.3 2304.13  4993.5 2303.63  4997.0 2303.63
  4997.3 2304.13  5013.7 2304.29  5022.4 2305.02  5072.9 2305.68  5079.0 2305.29
  5086.9 2305.85  5114.7 2311.48  5123.3 2312.55  5150.4 2313.94  5165.1 2320.45
  5169.8 2323.42  5172.6 2325.19  5179.9 2327.73  5194.7 2331.26  5221.0 2334.80
#Mann=6,-1,0
  4737.2    0.16       0  4764.7    0.07       0  4922.8   0.035       0
  4993.3   0.035       0  4997.3   0.035       0  5169.8    0.16       0
Bank Sta=4993.3,4997.3
Exp/Cntr=0.3,0.1

Type RM Length L Ch R = 1,20006,170,170,170
BEGIN DESCRIPTION:
Elm 52 20005.73
END DESCRIPTION:
XS GIS Cut Line= 3
      1508728.37      6763830.36      1508993.97      6763637.67
      1509150.12      6763453.76
#Sta/Elev= 30
  4660.7 2312.79  4688.8 2311.37  4723.5 2310.86  4789.4 2309.04  4795.5 2309.68
  4804.0 2308.93  4821.6 2308.93  4931.6 2307.42  4996.6 2304.21  5015.4 2300.81
  5015.7 2300.31  5019.2 2300.31  5019.4 2300.81  5039.4 2304.16  5057.5 2310.13
  5067.1 2313.17  5074.5 2313.68  5081.1 2313.08  5095.4 2313.31  5103.1 2314.35
  5109.7 2313.86  5117.4 2314.78  5187.7 2316.49  5195.4 2319.18  5201.9 2318.85
  5209.7 2322.03  5216.2 2321.46  5223.9 2324.86  5228.6 2324.40  5230.1 2324.25
#Mann=7,-1,0
  4660.7    0.16       0  4723.5    0.07       0  4821.6   0.035       0
  5015.4   0.035       0  5019.4   0.035       0  5057.5    0.07       0
  5228.6   0.035       0
Bank Sta=5015.4,5019.4
Exp/Cntr=0.3,0.1

Type RM Length L Ch R = 1,19836,93,93,93
BEGIN DESCRIPTION:
Elm 52 19836.06
END DESCRIPTION:
XS GIS Cut Line= 3
      1508971.39      6763889.42      1509106.82      6763738.37
      1509294.35      6763580.35
#Sta/Elev= 30
  4792.6 2306.05  4817.6 2304.77  4864.4 2303.55  4902.0 2301.55  4923.7 2301.54
  4930.4 2300.75  4952.1 2300.23  4958.8 2299.20  4966.3 2299.26  4973.1 2298.33
  4980.5 2298.48  4987.3 2296.99  4997.6 2297.69  4999.7 2296.78  5000.0 2296.28
  5003.5 2296.28  5003.7 2296.78  5016.0 2298.23  5030.3 2302.89  5051.2 2306.50
  5058.5 2306.22  5086.3 2308.64  5129.2 2310.22  5150.0 2309.98  5157.8 2309.24
  5164.3 2310.47  5172.1 2309.32  5178.6 2309.90  5186.4 2308.72  5240.7 2311.85
#Mann=4,-1,0
  4792.6   0.035       0  4864.4    0.07       0  4999.7    0.07       0
  5003.7    0.07       0
Bank Sta=4999.7,5003.7
Exp/Cntr=0.3,0.1

Type RM Length L Ch R = 1,19743,147,147,147
BEGIN DESCRIPTION:
Elm 52 19742.62
END DESCRIPTION:
XS GIS Cut Line= 3
      1509000.94      6763927.58      1509158.90      6763811.28
      1509320.14      6763726.33
#Sta/Elev= 30
  4809.0 2307.54  4833.1 2306.58  4847.8 2305.14  4861.1 2304.51  4868.6 2303.89
  4889.5 2304.17  4904.1 2303.35  4925.8 2300.24  4948.0 2299.00  4962.7 2299.48
  4975.5 2300.72  4989.7 2300.34  4998.2 2299.04  5010.0 2298.45  5010.3 2297.95
  5013.8 2297.95  5014.0 2298.45  5034.7 2301.47  5042.3 2301.22  5048.0 2302.19
  5056.8 2301.66  5064.4 2301.78  5070.0 2302.79  5086.4 2303.21  5092.1 2304.25
  5108.4 2304.29  5114.1 2305.20  5146.8 2305.99  5152.5 2306.64  5187.4 2307.77
#Mann=5,-1,0
  4809.0   0.035       0  4861.1    0.07       0  5010.0    0.07       0
  5014.0    0.07       0  5056.8    0.16       0
Bank Sta=5010,5014
Exp/Cntr=0.3,0.1

Type RM Length L Ch R = 1,19596,144,144,144
BEGIN DESCRIPTION:
Elm 52 19596.18
END DESCRIPTION:
XS GIS Cut Line= 3
      1509162.38      6764043.91      1509230.08      6763911.98
      1509342.92      6763743.58
#Sta/Elev= 30
  4852.5 2307.06  4867.0 2306.06  4872.6 2305.89  4894.8 2304.07  4926.6 2302.38
  4939.2 2300.70  4955.7 2299.30  4961.4 2299.14  4971.5 2297.52  4977.9 2293.18
  4992.0 2292.07  4992.3 2291.57  4995.8 2291.57  4996.0 2292.07  5000.1 2293.48
  5006.2 2293.78  5015.1 2295.07  5021.1 2295.54  5029.7 2296.75  5036.1 2298.23
  5042.1 2299.03  5057.1 2300.83  5073.8 2302.18  5108.2 2303.46  5114.2 2304.08
  5144.2 2305.14  5159.2 2305.97  5186.2 2306.72  5195.2 2307.40  5203.5 2307.68
#Mann=4,-1,0
  4852.5    0.07       0  4992.0    0.07       0  4996.0    0.07       0
  5073.8    0.16       0
Bank Sta=4992,4996
Exp/Cntr=0.3,0.1

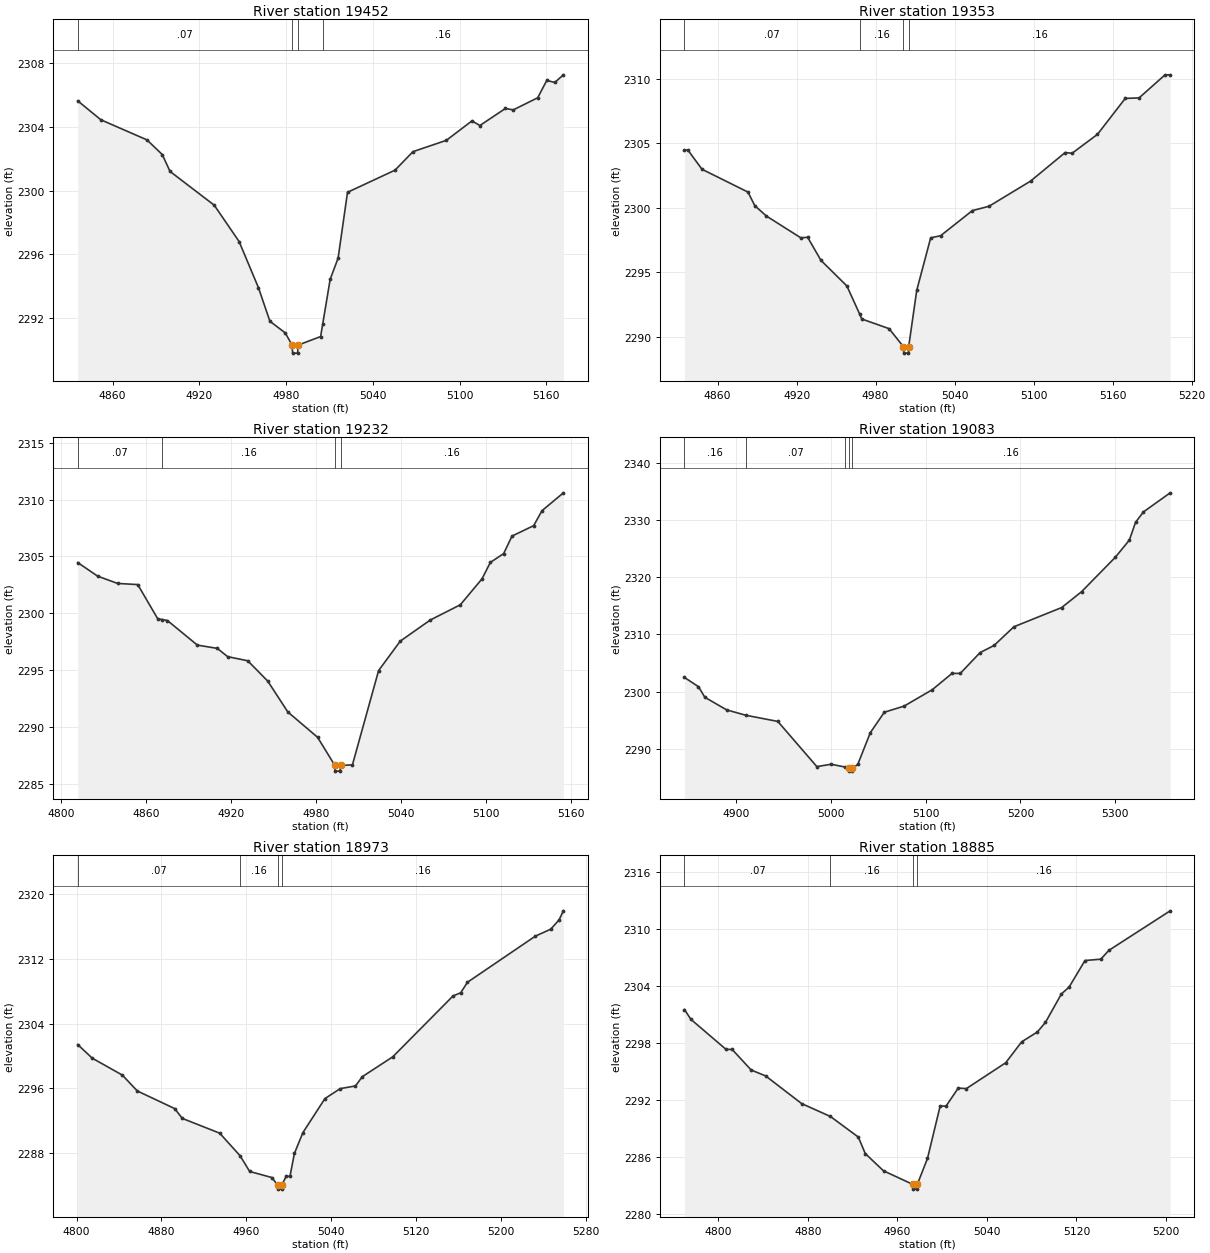
Type RM Length L Ch R = 1,19452,99,99,99
BEGIN DESCRIPTION:
Elm 52 19451.67
END DESCRIPTION:
XS GIS Cut Line= 3
      1509308.19      6764103.00      1509365.50      6763944.97
      1509434.36      6763791.73
#Sta/Elev= 30
  4835.8 2305.64  4851.8 2304.45  4883.7 2303.19  4894.3 2302.27  4899.7 2301.21
  4930.3 2299.09  4947.5 2296.81  4960.9 2293.91  4968.8 2291.81  4979.4 2291.08
  4984.2 2290.31  4984.5 2289.81  4988.0 2289.81  4988.2 2290.31  5003.9 2290.85
  5005.3 2291.61  5010.5 2294.44  5016.0 2295.77  5022.5 2299.90  5055.4 2301.29
  5067.8 2302.45  5090.9 2303.16  5108.6 2304.38  5114.1 2304.09  5131.8 2305.16
  5137.2 2305.07  5154.1 2305.83  5160.4 2306.92  5165.9 2306.79  5171.9 2307.27
#Mann=4,-1,0
  4835.8    0.07       0  4984.2    0.07       0  4988.2    0.07       0
  5005.3    0.16       0
Bank Sta=4984.2,4988.2
Exp/Cntr=0.3,0.1

Type RM Length L Ch R = 1,19353,121,121,121
BEGIN DESCRIPTION:
Elm 52 19352.65
END DESCRIPTION:
XS GIS Cut Line= 3
      1509407.16      6764148.08      1509448.83      6763991.84
      1509514.81      6763795.64
#Sta/Elev= 30
  4834.9 2304.47  4837.5 2304.47  4848.2 2302.98  4883.1 2301.21  4888.3 2300.15
  4897.1 2299.35  4923.2 2297.66  4928.4 2297.70  4938.5 2295.91  4958.2 2293.92
  4967.8 2291.76  4969.5 2291.36  4990.2 2290.61  5001.1 2289.21  5001.4 2288.71
  5004.9 2288.71  5005.1 2289.21  5011.2 2293.58  5021.8 2297.66  5029.3 2297.82
  5053.4 2299.77  5066.1 2300.11  5097.6 2302.06  5123.9 2304.28  5129.1 2304.22
  5148.4 2305.69  5169.5 2308.48  5180.0 2308.52  5199.7 2310.31  5203.6 2310.31
#Mann=4,-1,0
  4834.9    0.07       0  4967.8    0.16       0  5001.1    0.07       0
  5005.1    0.16       0
Bank Sta=5001.1,5005.1
Exp/Cntr=0.3,0.1

Type RM Length L Ch R = 1,19232,149,149,149
BEGIN DESCRIPTION:
Elm 52 19232.08
END DESCRIPTION:
XS GIS Cut Line= 3
      1509426.26      6764168.93      1509559.94      6764028.30
      1509639.36      6763902.26
#Sta/Elev= 30
  4811.6 2304.46  4825.7 2303.26  4839.8 2302.62  4854.0 2302.52  4868.1 2299.51
  4871.3 2299.44  4875.0 2299.35  4896.1 2297.19  4910.2 2296.90  4917.5 2296.17
  4931.7 2295.81  4945.8 2294.02  4960.0 2291.30  4981.0 2289.07  4993.2 2286.59
  4993.4 2286.09  4996.9 2286.09  4997.2 2286.59  5005.6 2286.64  5024.1 2294.95
  5039.4 2297.54  5060.6 2299.40  5081.8 2300.74  5097.1 2303.02  5103.0 2304.47
  5112.4 2305.25  5118.3 2306.79  5133.6 2307.71  5139.5 2309.03  5154.6 2310.60
#Mann=4,-1,0
  4811.6    0.07       0  4871.3    0.16       0  4993.2    0.07       0
  4997.2    0.16       0
Bank Sta=4993.2,4997.2
Exp/Cntr=0.3,0.1

Type RM Length L Ch R = 1,19083,110,110,110
BEGIN DESCRIPTION:
Elm 52 19082.999
END DESCRIPTION:
XS GIS Cut Line= 3
      1509505.04      6764187.98      1509649.08      6764130.99
      1509854.99      6763838.02
#Sta/Elev= 30
  4845.1 2302.46  4859.9 2300.85  4866.6 2299.00  4889.6 2296.80  4909.9 2295.86
  4943.7 2294.78  4984.9 2286.89  5000.0 2287.30  5014.9 2286.81  5018.5 2286.60
  5018.7 2286.10  5022.2 2286.10  5022.5 2286.60  5028.1 2287.26  5041.4 2292.82
  5056.2 2296.39  5077.1 2297.46  5106.8 2300.32  5127.7 2303.17  5136.4 2303.17
  5157.3 2306.80  5172.1 2308.05  5193.0 2311.31  5243.5 2314.67  5264.5 2317.44
  5300.2 2323.46  5315.0 2326.46  5321.5 2329.55  5329.8 2331.37  5358.1 2334.71
#Mann=5,-1,0
  4845.1    0.16       0  4909.9    0.07       0  5014.9    0.16       0
  5018.5    0.07       0  5022.5    0.16       0
Bank Sta=5018.5,5022.5
Exp/Cntr=0.3,0.1

Type RM Length L Ch R = 1,18973,88,88,88
BEGIN DESCRIPTION:
Elm 52 18972.83
END DESCRIPTION:
XS GIS Cut Line= 3
      1509592.93      6764325.17      1509738.76      6764188.02
      1509900.09      6763986.79
#Sta/Elev= 30
  4801.0 2301.41  4814.7 2299.73  4843.1 2297.64  4857.2 2295.68  4892.4 2293.51
  4899.7 2292.29  4934.9 2290.47  4954.1 2287.69  4963.2 2285.74  4984.2 2284.99
  4989.5 2284.06  4989.8 2283.56  4993.3 2283.56  4993.5 2284.06  4997.6 2285.14
  5001.2 2285.14  5005.4 2287.97  5013.4 2290.54  5034.2 2294.74  5048.6 2295.97
  5063.0 2296.30  5069.4 2297.44  5098.2 2299.90  5155.0 2307.41  5162.2 2307.80
  5168.6 2309.10  5232.7 2314.80  5247.1 2315.65  5255.0 2316.80  5259.1 2317.92
#Mann=4,-1,0
  4801.0    0.07       0  4954.1    0.16       0  4989.5    0.07       0
  4993.5    0.16       0
Bank Sta=4989.5,4993.5
Exp/Cntr=0.3,0.1

Type RM Length L Ch R = 1,18885,124,124,124
BEGIN DESCRIPTION:
Elm 52 18885.05
END DESCRIPTION:
XS GIS Cut Line= 3
      1509599.86      6764340.80      1509809.94      6764238.37
      1509954.07      6764099.45
#Sta/Elev= 30
  4769.9 2301.53  4775.6 2300.50  4807.0 2297.33  4812.5 2297.32  4829.5 2295.15
  4842.4 2294.53  4874.6 2291.61  4900.3 2290.25  4925.2 2288.08  4931.4 2286.34
  4947.7 2284.52  4973.9 2283.09  4974.1 2282.59  4977.6 2282.59  4977.9 2283.09
  4987.0 2285.83  4998.3 2291.35  5003.6 2291.35  5014.5 2293.25  5021.7 2293.19
  5056.9 2295.92  5071.1 2298.12  5085.2 2299.17  5092.4 2300.18  5106.6 2303.17
  5113.5 2303.90  5127.7 2306.70  5141.8 2306.84  5149.0 2307.77  5203.8 2311.94
#Mann=4,-1,0
  4769.9    0.07       0  4900.3    0.16       0  4973.9    0.07       0
  4977.9    0.16       0
Bank Sta=4973.9,4977.9
Exp/Cntr=0.3,0.1

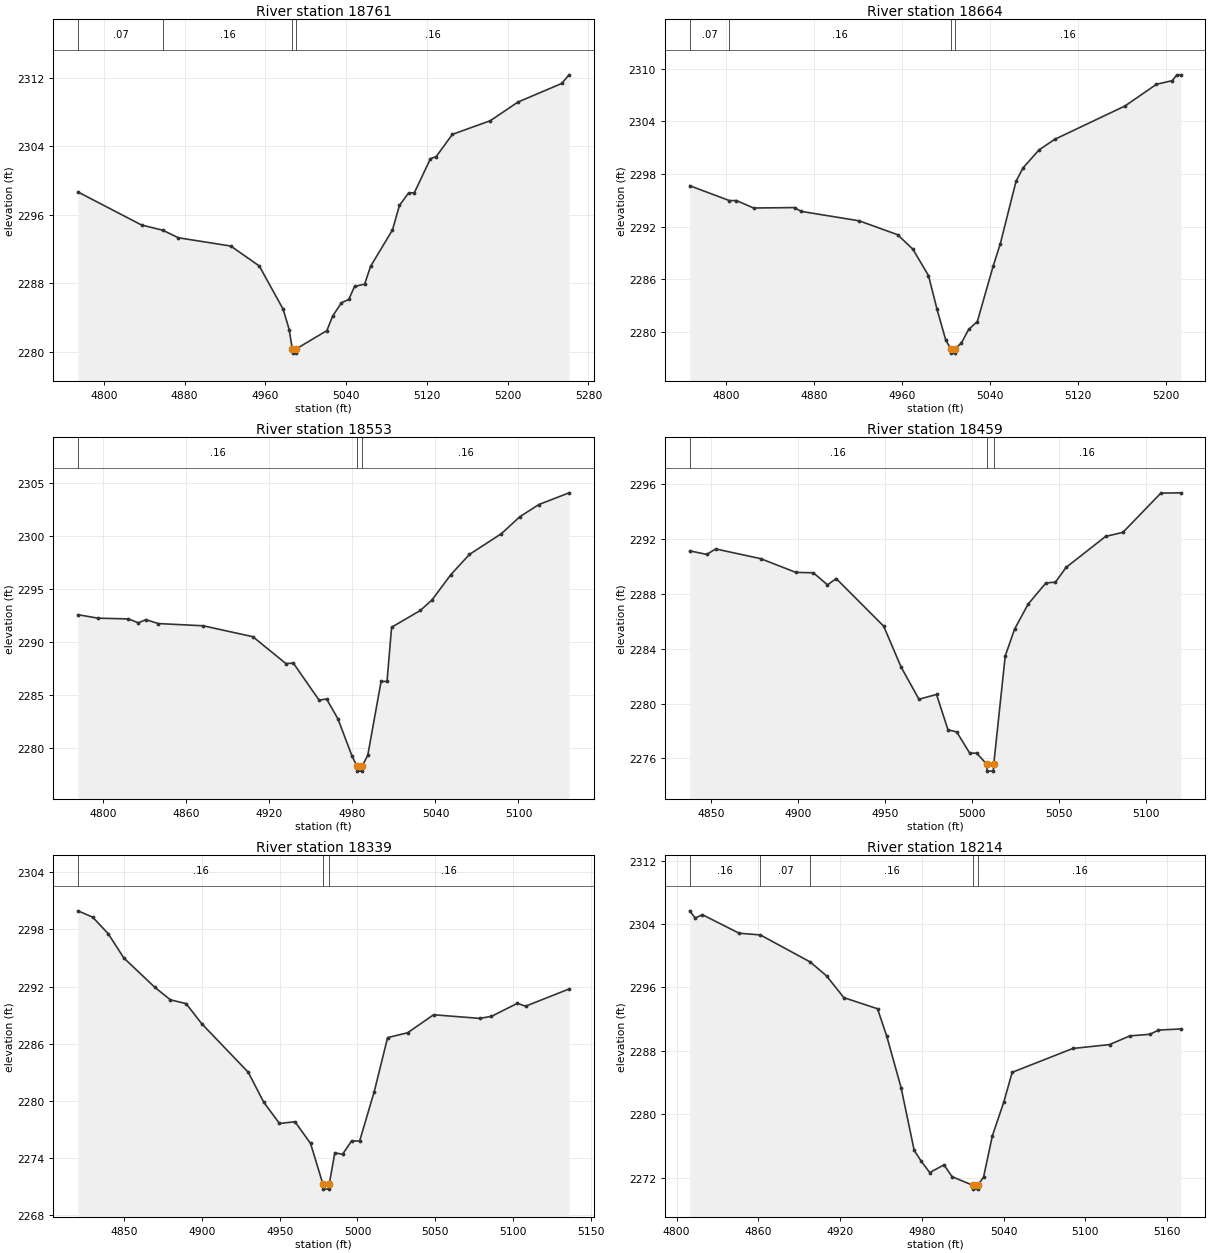
Type RM Length L Ch R = 1,18761,97,97,97
BEGIN DESCRIPTION:
Elm 52 18761.21
END DESCRIPTION:
XS GIS Cut Line= 3
      1509672.80      6764464.06      1509858.55      6764347.74
      1510091.42      6764216.65
#Sta/Elev= 30
  4774.4 2298.64  4837.4 2294.78  4858.4 2294.17  4873.9 2293.29  4925.8 2292.32
  4954.0 2289.99  4977.6 2284.94  4983.6 2282.57  4986.6 2280.31  4986.9 2279.81
  4990.4 2279.81  4990.6 2280.31  5020.9 2282.44  5026.6 2284.13  5035.4 2285.70
  5042.6 2286.08  5048.3 2287.60  5058.3 2287.87  5064.2 2289.95  5085.9 2294.21
  5092.8 2297.07  5101.8 2298.52  5107.6 2298.56  5123.5 2302.53  5129.2 2302.78
  5145.2 2305.37  5182.8 2306.97  5210.2 2309.15  5253.5 2311.32  5260.8 2312.33
#Mann=4,-1,0
  4774.4    0.07       0  4858.4    0.16       0  4986.6    0.07       0
  4990.6    0.16       0
Bank Sta=4986.6,4990.6
Exp/Cntr=0.3,0.1

Type RM Length L Ch R = 1,18664,111,111,111
BEGIN DESCRIPTION:
Elm 52 18664.25
END DESCRIPTION:
XS GIS Cut Line= 3
      1509731.85      6764533.49      1509919.32      6764424.13
      1510096.37      6764278.32
#Sta/Elev= 30
  4766.9 2296.68  4803.0 2294.98  4809.3 2294.99  4825.0 2294.14  4862.2 2294.19
  4868.0 2293.76  4920.9 2292.68  4955.8 2291.10  4969.7 2289.45  4983.9 2286.45
  4991.7 2282.59  4999.6 2279.10  5004.1 2278.11  5004.3 2277.61  5007.8 2277.61
  5008.1 2278.11  5013.9 2278.78  5020.4 2280.31  5028.3 2281.21  5042.6 2287.48
  5049.1 2290.04  5063.5 2297.19  5069.9 2298.72  5084.3 2300.75  5098.6 2301.96
  5162.5 2305.76  5191.1 2308.23  5205.5 2308.65  5209.6 2309.31  5213.3 2309.31
#Mann=4,-1,0
  4766.9    0.07       0  4803.0    0.16       0  5004.1    0.07       0
  5008.1    0.16       0
Bank Sta=5004.1,5008.1
Exp/Cntr=0.3,0.1

Type RM Length L Ch R = 1,18553,94,94,94
BEGIN DESCRIPTION:
Elm 52 18553.42
END DESCRIPTION:
XS GIS Cut Line= 3
      1509801.29      6764580.37      1510007.86      6764495.31
      1510113.76      6764417.18
#Sta/Elev= 30
  4781.6 2292.58  4796.0 2292.25  4818.1 2292.18  4825.3 2291.81  4830.7 2292.11
  4839.7 2291.74  4872.1 2291.53  4908.0 2290.50  4931.9 2287.96  4937.3 2288.00
  4955.9 2284.50  4961.3 2284.61  4969.5 2282.74  4979.8 2279.18  4983.2 2278.29
  4983.5 2277.79  4987.0 2277.79  4987.2 2278.29  4991.1 2279.30  5000.7 2286.27
  5005.0 2286.27  5008.3 2291.39  5029.1 2292.98  5037.5 2293.97  5051.1 2296.36
  5064.6 2298.28  5087.7 2300.24  5100.9 2301.83  5114.7 2302.99  5136.6 2304.10
#Mann=3,-1,0
  4781.6    0.16       0  4983.2    0.07       0  4987.2    0.16       0
Bank Sta=4983.2,4987.2
Exp/Cntr=0.3,0.1

Type RM Length L Ch R = 1,18459,120,120,120
BEGIN DESCRIPTION:
Elm 52 18459.35
END DESCRIPTION:
XS GIS Cut Line= 3
      1509844.68      6764615.10      1510007.86      6764590.80
      1510115.51      6764543.92
#Sta/Elev= 30
  4837.6 2291.13  4847.4 2290.87  4852.5 2291.27  4878.4 2290.56  4898.6 2289.56
  4908.7 2289.53  4916.8 2288.65  4921.8 2289.11  4949.1 2285.64  4959.2 2282.64
  4969.4 2280.31  4979.5 2280.66  4986.1 2278.08  4991.1 2277.93  4998.6 2276.38
  5002.6 2276.38  5008.4 2275.57  5008.6 2275.07  5012.1 2275.07  5012.4 2275.57
  5019.0 2283.46  5024.4 2285.43  5032.2 2287.25  5042.4 2288.79  5047.9 2288.85
  5054.0 2289.92  5076.7 2292.18  5086.7 2292.48  5108.5 2295.34  5120.0 2295.36
#Mann=3,-1,0
  4837.6    0.16       0  5008.4    0.07       0  5012.4    0.16       0
Bank Sta=5008.4,5012.4
Exp/Cntr=0.3,0.1

Type RM Length L Ch R = 1,18339,125,125,125
BEGIN DESCRIPTION:
Elm 52 18339.14
END DESCRIPTION:
XS GIS Cut Line= 3
      1509825.57      6764722.74      1510002.65      6764712.33
      1510131.44      6764660.81
#Sta/Elev= 30
  4820.1 2299.96  4829.6 2299.29  4839.6 2297.55  4849.6 2295.01  4869.6 2291.92
  4879.6 2290.61  4889.7 2290.21  4899.7 2288.11  4929.7 2283.00  4939.7 2279.84
  4949.8 2277.62  4959.8 2277.80  4969.8 2275.52  4977.8 2271.22  4978.1 2270.72
  4981.6 2270.72  4981.8 2271.22  4985.4 2274.52  4990.4 2274.39  4996.2 2275.78
  5001.4 2275.78  5010.8 2280.97  5019.4 2286.64  5032.3 2287.15  5049.0 2289.04
  5078.6 2288.66  5086.2 2288.87  5102.9 2290.24  5108.2 2289.94  5136.2 2291.75
#Mann=3,-1,0
  4820.1    0.16       0  4977.8    0.07       0  4981.8    0.16       0
Bank Sta=4977.8,4981.8
Exp/Cntr=0.3,0.1

Type RM Length L Ch R = 1,18214,98,98,98
BEGIN DESCRIPTION:
Elm 52 18213.73
END DESCRIPTION:
XS GIS Cut Line= 3
      1509827.32      6764894.61      1510011.33      6764835.59
      1510148.51      6764740.08
#Sta/Elev= 30
  4809.7 2305.66  4813.7 2304.75  4819.0 2305.17  4845.9 2302.84  4861.5 2302.62
  4898.2 2299.20  4910.1 2297.45  4922.8 2294.71  4947.5 2293.31  4954.3 2289.83
  4964.8 2283.35  4974.4 2275.45  4979.6 2274.07  4985.8 2272.65  4996.3 2273.62
  5002.2 2272.13  5017.2 2271.06  5017.5 2270.56  5021.0 2270.56  5021.2 2271.06
  5025.3 2272.07  5031.8 2277.30  5040.2 2281.56  5046.3 2285.29  5090.8 2288.30
  5117.8 2288.79  5132.7 2289.89  5147.5 2290.09  5153.6 2290.62  5170.1 2290.76
#Mann=5,-1,0
  4809.7    0.16       0  4861.5    0.07       0  4898.2    0.16       0
  5017.2    0.07       0  5021.2    0.16       0
Bank Sta=5017.2,5021.2
Exp/Cntr=0.3,0.1