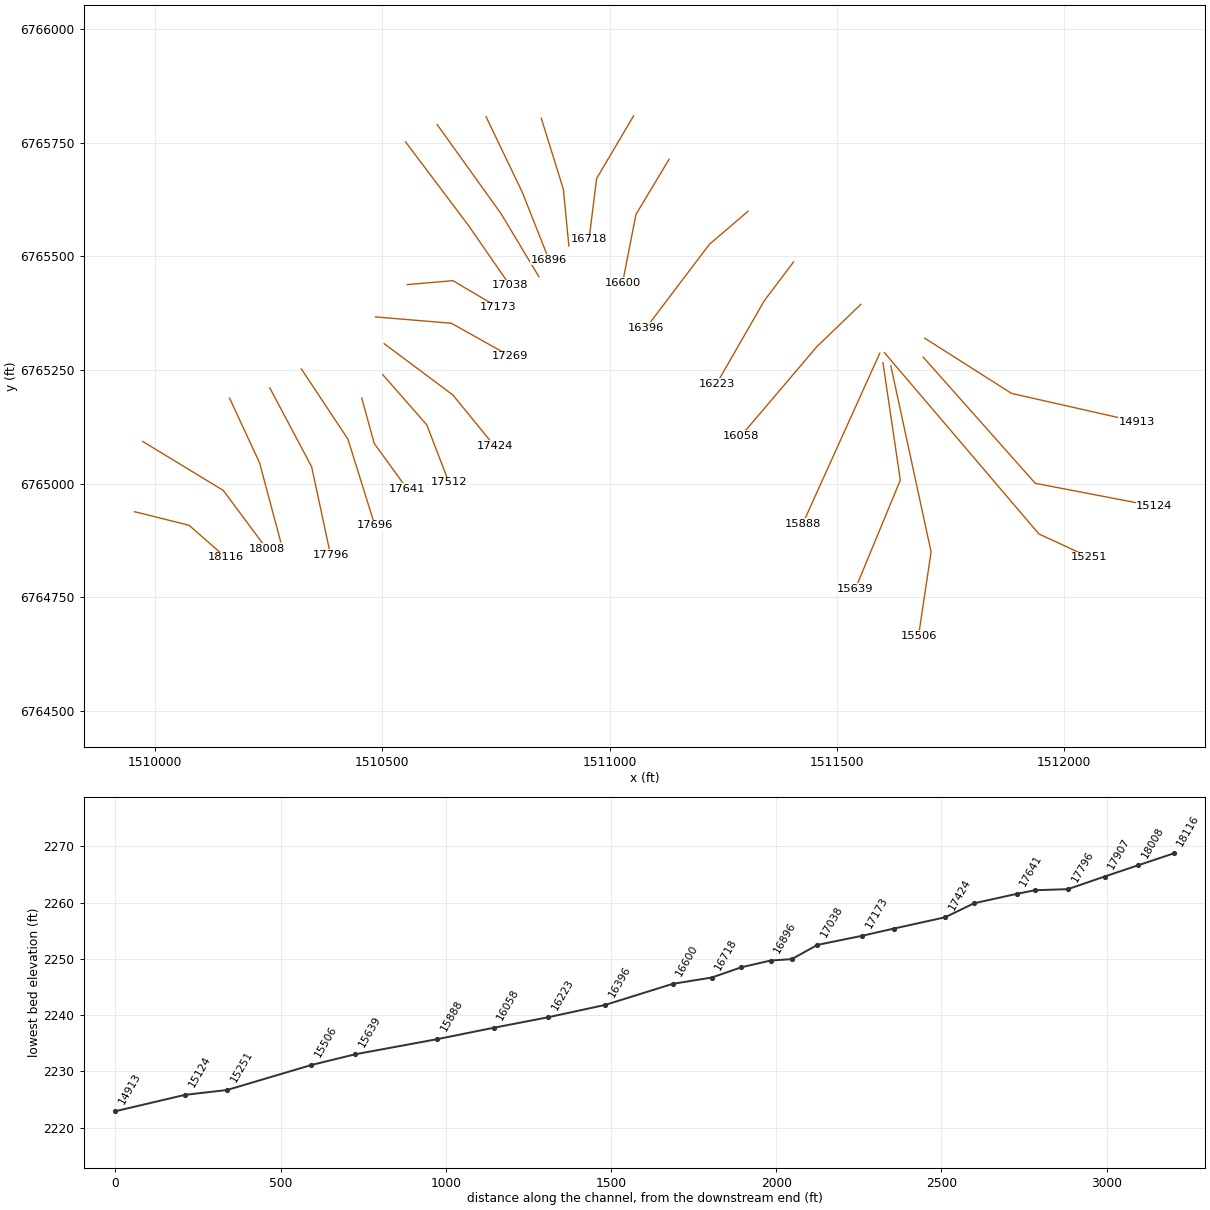
HEC-RAS study Elm 52.prj: Elm 52 Base Level Engineering

--- Elm 52.g01 (geometry) --- (continued)

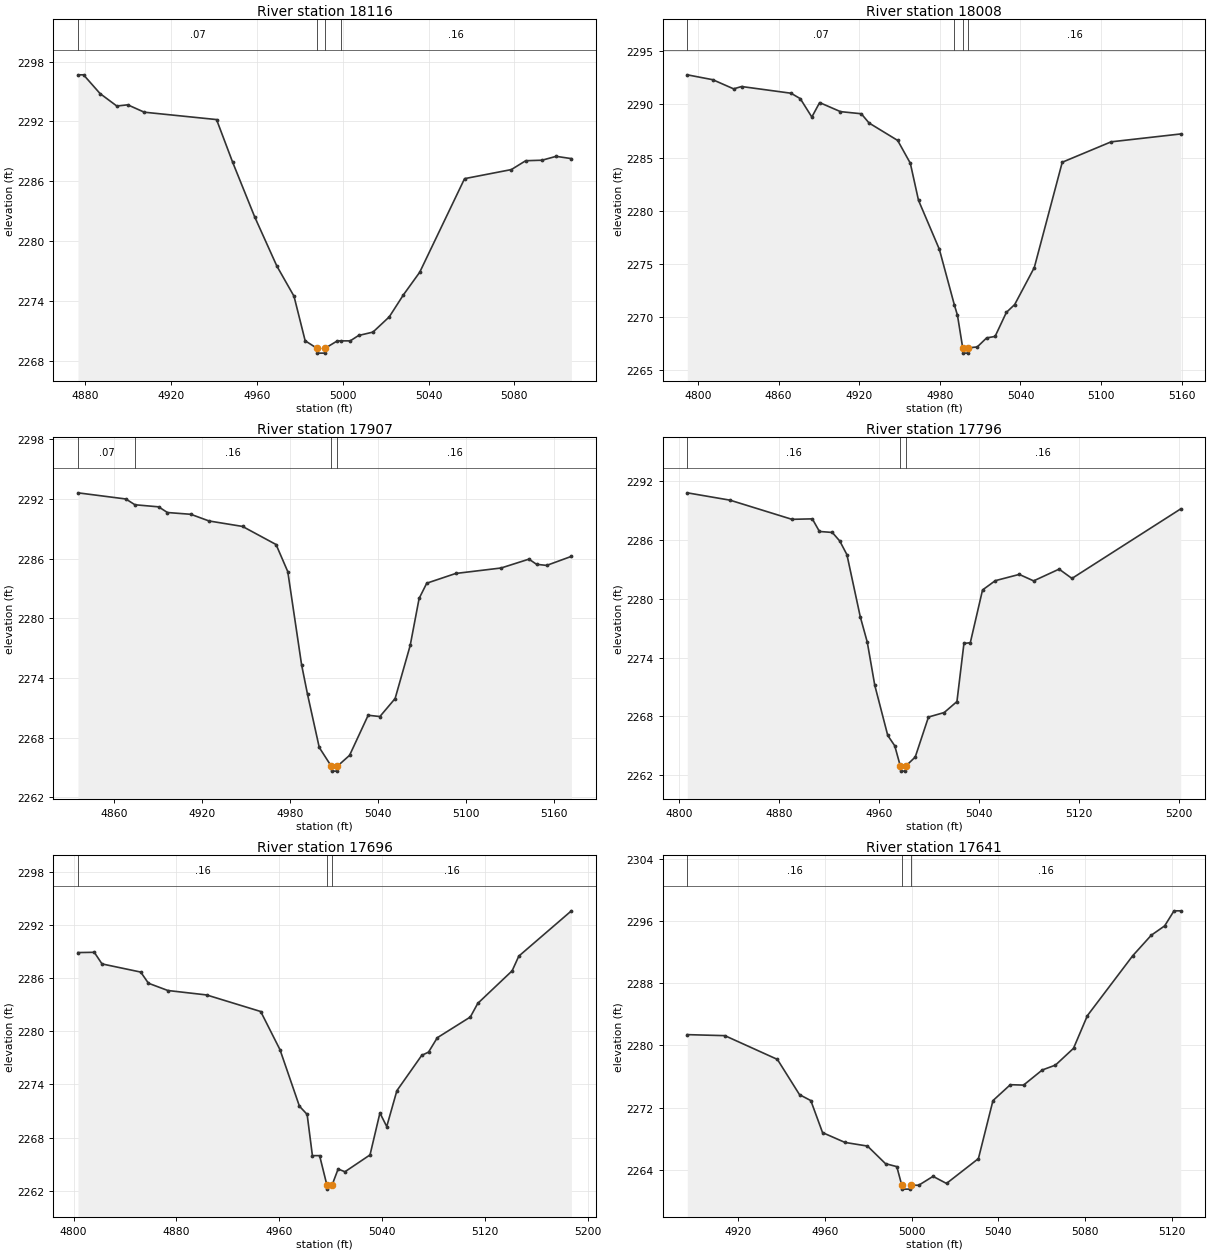
Type RM Length L Ch R = 1,18116,108,108,108
BEGIN DESCRIPTION:
Elm 52 18115.83
END DESCRIPTION:
XS GIS Cut Line= 3
      1509955.02      6764937.99      1510074.78      6764908.22
      1510154.99      6764838.01
#Sta/Elev= 30
  4876.6 2296.67  4879.2 2296.67  4886.9 2294.79  4894.7 2293.54  4899.8 2293.66
  4907.5 2292.92  4941.2 2292.18  4948.7 2287.90  4959.0 2282.40  4969.3 2277.48
  4977.3 2274.45  4982.5 2269.98  4987.9 2269.24  4988.2 2268.74  4991.7 2268.74
  4991.9 2269.24  4997.5 2269.97  4999.3 2269.97  5003.5 2269.97  5007.4 2270.51
  5014.1 2270.85  5021.7 2272.38  5028.3 2274.59  5035.9 2276.86  5056.8 2286.25
  5078.6 2287.16  5085.3 2288.05  5092.9 2288.10  5099.5 2288.49  5106.6 2288.26
#Mann=4,-1,0
  4876.6    0.07       0  4987.9    0.07       0  4991.9    0.07       0
  4999.3    0.16       0
Bank Sta=4987.9,4991.9
Exp/Cntr=0.3,0.1

Type RM Length L Ch R = 1,18008,101,101,101
BEGIN DESCRIPTION:
Elm 52 18008.38
END DESCRIPTION:
XS GIS Cut Line= 3
      1509973.13      6765092.54      1510150.22      6764984.90
      1510245.70      6764856.43
#Sta/Elev= 30
  4792.0 2292.79  4811.0 2292.33  4826.5 2291.47  4832.4 2291.69  4869.2 2291.06
  4876.1 2290.55  4884.7 2288.82  4890.5 2290.18  4906.0 2289.33  4921.5 2289.13
  4927.3 2288.26  4948.6 2286.62  4958.0 2284.48  4964.1 2280.99  4979.6 2276.39
  4990.8 2271.15  4993.1 2270.18  4997.0 2267.12  4997.3 2266.62  5000.9 2266.62
  5001.2 2267.12  5007.8 2267.20  5014.8 2268.05  5021.1 2268.19  5029.5 2270.45
  5035.7 2271.19  5050.3 2274.67  5071.1 2284.57  5107.5 2286.49  5159.3 2287.23
#Mann=4,-1,0
  4792.0    0.07       0  4990.8    0.16       0  4997.0    0.07       0
  5001.2    0.16       0
Bank Sta=4997,5001.2
Exp/Cntr=0.3,0.1

Type RM Length L Ch R = 1,17907,111,111,111
BEGIN DESCRIPTION:
Elm 52 17907.22
END DESCRIPTION:
XS GIS Cut Line= 3
      1510164.12      6765187.99      1510230.08      6765045.66
      1510276.60      6764871.64
#Sta/Elev= 30
  4835.2 2292.62  4867.9 2292.00  4874.1 2291.42  4890.3 2291.21  4896.3 2290.64
  4912.3 2290.46  4924.7 2289.79  4947.6 2289.24  4970.5 2287.42  4978.5 2284.69
  4987.9 2275.35  4992.0 2272.34  5000.0 2267.01  5008.2 2265.13  5008.5 2264.63
  5012.1 2264.63  5012.4 2265.13  5020.7 2266.22  5033.4 2270.25  5041.4 2270.12
  5051.8 2271.93  5062.1 2277.27  5068.2 2282.00  5073.4 2283.53  5093.2 2284.51
  5124.2 2285.06  5143.2 2285.95  5148.4 2285.43  5155.3 2285.32  5172.2 2286.23
#Mann=4,-1,0
  4835.2    0.07       0  4874.1    0.16       0  5008.2    0.07       0
  5012.4    0.16       0
Bank Sta=5008.2,5012.4
Exp/Cntr=0.3,0.1

Type RM Length L Ch R = 1,17796,100,100,100
BEGIN DESCRIPTION:
Elm 52 17795.99
END DESCRIPTION:
XS GIS Cut Line= 3
      1510252.64      6765210.61      1510344.66      6765036.98
      1510386.27      6764842.80
#Sta/Elev= 30
  4806.5 2290.84  4840.7 2290.09  4890.3 2288.13  4906.6 2288.18  4912.3 2286.89
  4922.6 2286.79  4928.6 2285.91  4934.3 2284.52  4945.0 2278.17  4950.6 2275.58
  4956.6 2271.17  4967.0 2266.04  4972.6 2264.98  4977.1 2262.89  4977.4 2262.39
  4981.1 2262.39  4981.3 2262.89  4989.0 2263.83  4999.6 2267.92  5012.2 2268.38
  5022.4 2269.50  5028.0 2275.44  5033.1 2275.52  5042.9 2280.91  5053.1 2281.86
  5072.3 2282.50  5083.8 2281.84  5104.2 2283.04  5114.5 2282.09  5201.6 2289.20
#Mann=3,-1,0
  4806.5    0.16       0  4977.1    0.07       0  4981.3    0.16       0
Bank Sta=4977.1,4981.3
Exp/Cntr=0.3,0.1

Type RM Length L Ch R = 1,17696,55,55,55
BEGIN DESCRIPTION:
Elm 52 17695.83
END DESCRIPTION:
XS GIS Cut Line= 3
      1510322.07      6765252.29      1510424.52      6765097.74
      1510483.57      6764908.46
#Sta/Elev= 30
  4803.4 2288.88  4816.1 2288.91  4822.1 2287.60  4852.2 2286.68  4858.2 2285.42
  4873.3 2284.60  4903.4 2284.10  4945.5 2282.23  4960.5 2277.92  4975.6 2271.55
  4981.6 2270.62  4985.7 2265.97  4991.3 2265.97  4996.9 2262.69  4997.2 2262.19
  5001.1 2262.69  5005.7 2264.46  5011.0 2264.15  5030.5 2266.05  5038.2 2270.78
  5043.5 2269.25  5051.4 2273.30  5070.7 2277.28  5076.0 2277.65  5082.8 2279.27
  5108.5 2281.61  5114.3 2283.15  5141.0 2286.82  5146.2 2288.48  5187.1 2293.59
#Mann=3,-1,0
  4803.4    0.16       0  4996.9    0.07       0  5001.1    0.16       0
Bank Sta=4996.9,5001.1
Exp/Cntr=0.3,0.1

Type RM Length L Ch R = 1,17641,129,129,129
BEGIN DESCRIPTION:
Elm 52 17641.327
END DESCRIPTION:
XS GIS Cut Line= 3
      1510454.99      6765188.03      1510482.33      6765088.42
      1510555.03      6764987.96
#Sta/Elev= 30
  4896.7 2281.39  4914.0 2281.26  4938.2 2278.21  4948.4 2273.68  4953.6 2272.92
  4959.0 2268.81  4969.3 2267.55  4979.7 2267.08  4988.0 2264.82  4993.2 2264.44
  4995.5 2262.05  4995.8 2261.55  4999.5 2261.55  4999.7 2262.05  5003.3 2262.05
  5009.9 2263.19  5016.1 2262.28  5030.8 2265.47  5037.5 2272.92  5045.5 2274.96
  5051.6 2274.91  5060.2 2276.85  5066.3 2277.48  5074.6 2279.63  5081.0 2283.83
  5101.9 2291.53  5110.4 2294.15  5116.6 2295.36  5120.9 2297.29  5124.0 2297.29
#Mann=3,-1,0
  4896.7    0.16       0  4995.5    0.07       0  4999.7    0.16       0
Bank Sta=4995.5,4999.7
Exp/Cntr=0.3,0.1

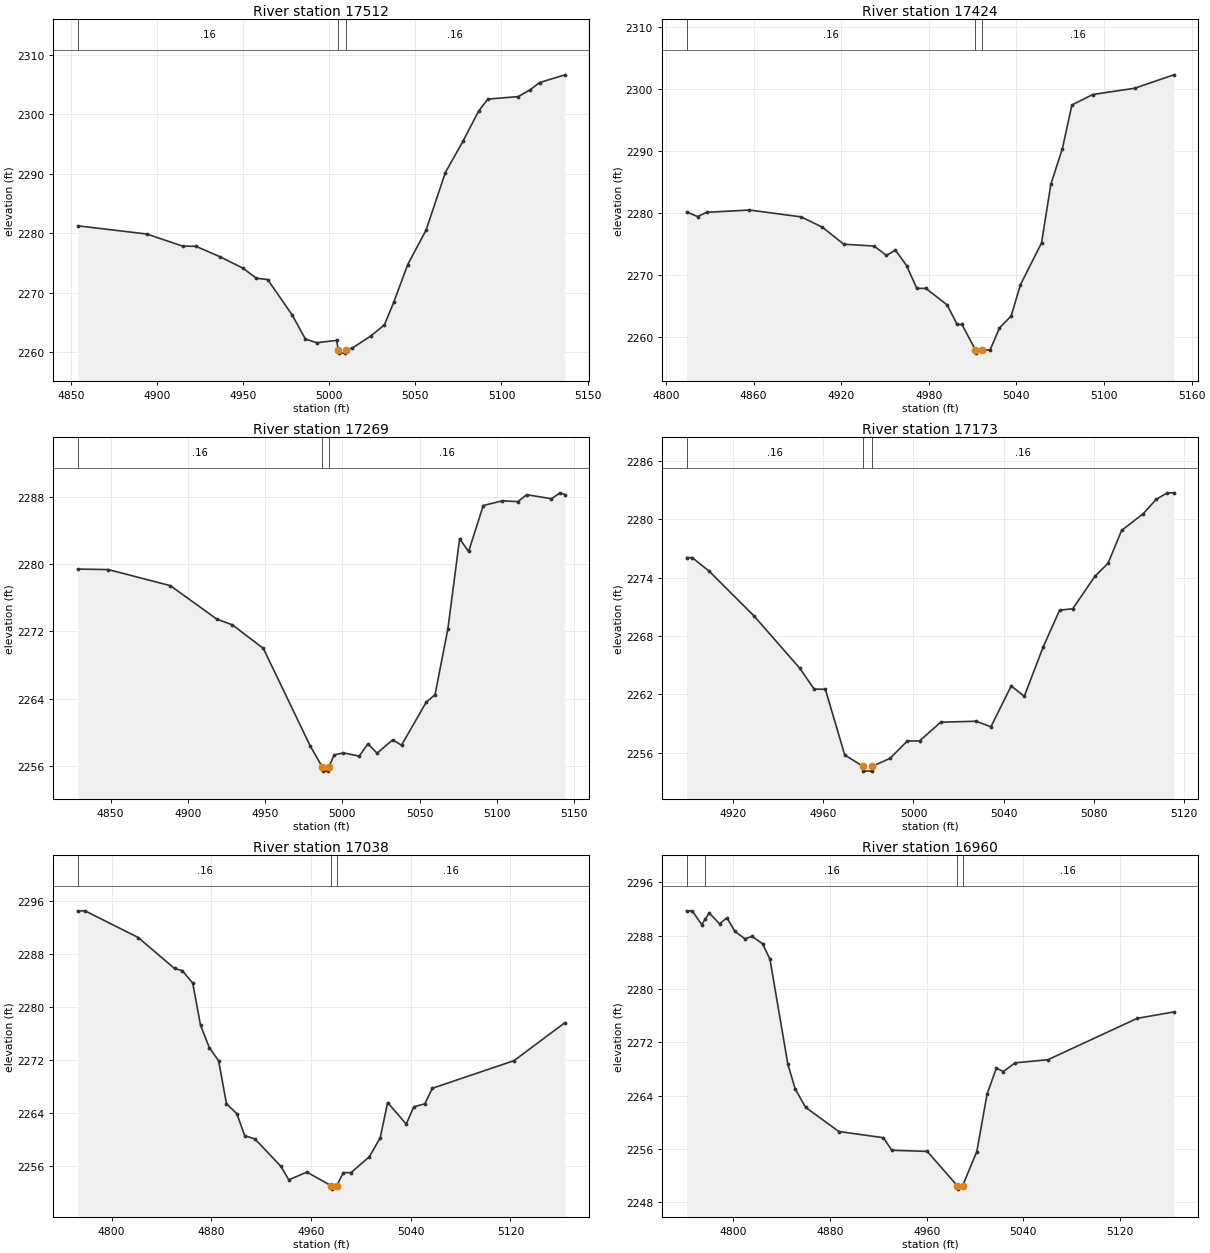
Type RM Length L Ch R = 1,17512,88,88,88
BEGIN DESCRIPTION:
Elm 52 17511.63
END DESCRIPTION:
XS GIS Cut Line= 3
      1510500.90      6765240.11      1510598.13      6765128.99
      1510646.60      6765002.62
#Sta/Elev= 30
  4853.9 2281.28  4894.0 2279.90  4914.9 2277.86  4922.5 2277.84  4936.4 2276.10
  4950.0 2274.13  4957.6 2272.47  4964.2 2272.25  4978.5 2266.26  4986.1 2262.25
  4992.7 2261.63  5004.2 2262.02  5005.3 2260.38  5005.5 2259.88  5009.2 2259.88
  5009.5 2260.38  5013.3 2260.72  5024.0 2262.74  5032.0 2264.62  5037.4 2268.41
  5045.5 2274.74  5056.2 2280.56  5067.4 2290.24  5077.6 2295.48  5086.7 2300.56
  5092.1 2302.58  5109.7 2303.00  5116.8 2304.17  5122.1 2305.36  5136.9 2306.66
#Mann=3,-1,0
  4853.9    0.16       0  5005.3    0.07       0  5009.5    0.16       0
Bank Sta=5005.3,5009.5
Exp/Cntr=0.3,0.1

Type RM Length L Ch R = 1,17424,155,155,155
BEGIN DESCRIPTION:
Elm 52 17423.57
END DESCRIPTION:
XS GIS Cut Line= 3
      1510504.39      6765307.81      1510655.43      6765194.97
      1510747.10      6765082.54
#Sta/Elev= 30
  4814.2 2280.19  4821.7 2279.43  4828.0 2280.11  4857.2 2280.49  4892.6 2279.38
  4907.2 2277.71  4921.8 2274.97  4942.6 2274.67  4951.0 2273.16  4957.2 2274.01
  4964.8 2271.52  4971.8 2267.84  4978.0 2267.84  4992.6 2265.16  4999.4 2262.02
  5002.7 2262.02  5012.0 2257.88  5012.2 2257.38  5016.2 2257.88  5022.0 2257.89
  5028.4 2261.44  5036.4 2263.37  5042.8 2268.44  5057.2 2275.17  5063.6 2284.65
  5071.5 2290.42  5078.0 2297.45  5092.3 2299.14  5121.1 2300.16  5147.8 2302.32
#Mann=3,-1,0
  4814.2    0.16       0  5012.0    0.07       0  5016.2    0.16       0
Bank Sta=5012,5016.2
Exp/Cntr=0.3,0.1

Type RM Length L Ch R = 1,17269,96,96,96
BEGIN DESCRIPTION:
Elm 52 17269.03
END DESCRIPTION:
XS GIS Cut Line= 3
      1510485.27      6765366.84      1510651.95      6765352.95
      1510781.12      6765280.62
#Sta/Elev= 30
  4828.8 2279.39  4848.6 2279.33  4888.7 2277.42  4918.8 2273.44  4928.9 2272.76
  4948.9 2269.96  4979.1 2258.42  4987.0 2255.88  4987.2 2255.38  4990.9 2255.38
  4991.2 2255.88  4994.8 2257.31  5000.7 2257.55  5010.9 2257.16  5016.6 2258.62
  5022.5 2257.51  5032.6 2259.10  5038.3 2258.46  5054.2 2263.54  5060.0 2264.48
  5068.3 2272.28  5075.9 2282.99  5081.7 2281.48  5091.2 2286.94  5103.4 2287.50
  5113.6 2287.41  5119.3 2288.23  5135.3 2287.75  5141.0 2288.45  5144.1 2288.24
#Mann=3,-1,0
  4828.8    0.16       0  4987.0    0.07       0  4991.2    0.16       0
Bank Sta=4987,4991.2
Exp/Cntr=0.3,0.1

Type RM Length L Ch R = 1,17173,135,135,135
BEGIN DESCRIPTION:
Elm 52 17173.379
END DESCRIPTION:
XS GIS Cut Line= 3
      1510555.03      6765438.00      1510655.36      6765446.68
      1510754.97      6765388.02
#Sta/Elev= 30
  4899.3 2276.05  4901.8 2276.05  4909.3 2274.66  4929.4 2270.01  4949.5 2264.69
  4955.9 2262.54  4960.9 2262.51  4969.5 2255.77  4977.5 2254.60  4977.7 2254.10
  4981.4 2254.10  4981.7 2254.60  4989.6 2255.41  4997.3 2257.20  5002.7 2257.20
  5012.1 2259.13  5027.8 2259.23  5034.4 2258.66  5043.4 2262.86  5049.2 2261.79
  5057.6 2266.87  5064.9 2270.65  5070.7 2270.79  5080.6 2274.14  5086.4 2275.47
  5092.4 2278.84  5102.0 2280.56  5107.8 2282.05  5112.7 2282.71  5115.6 2282.71
#Mann=3,-1,0
  4899.3    0.16       0  4977.5    0.07       0  4981.7    0.16       0
Bank Sta=4977.5,4981.7
Exp/Cntr=0.3,0.1

Type RM Length L Ch R = 1,17038,78,78,78
BEGIN DESCRIPTION:
Elm 52 17037.99
END DESCRIPTION:
XS GIS Cut Line= 3
      1510551.25      6765752.27      1510688.41      6765569.97
      1510781.05      6765436.15
#Sta/Elev= 30
  4772.9 2294.48  4778.7 2294.48  4821.4 2290.45  4850.5 2285.78  4856.8 2285.44
  4865.1 2283.58  4871.4 2277.20  4878.4 2273.85  4885.9 2271.84  4892.2 2265.36
  4900.5 2263.87  4906.8 2260.56  4915.1 2260.04  4935.9 2255.91  4942.2 2253.88
  4956.7 2255.05  4976.3 2252.98  4976.6 2252.48  4980.6 2252.98  4985.9 2254.96
  4992.2 2254.98  5006.7 2257.35  5015.5 2260.20  5021.5 2265.55  5036.4 2262.30
  5042.5 2264.90  5051.3 2265.36  5057.4 2267.70  5122.9 2271.87  5163.8 2277.61
#Mann=3,-1,0
  4772.9    0.16       0  4976.3    0.07       0  4980.6    0.16       0
Bank Sta=4976.3,4980.6
Exp/Cntr=0.3,0.1

Type RM Length L Ch R = 1,16960,64,64,64
BEGIN DESCRIPTION:
Elm 52 16959.84
END DESCRIPTION:
XS GIS Cut Line= 3
      1510620.72      6765790.43      1510761.33      6765594.27
      1510844.65      6765455.40
#Sta/Elev= 30
  4761.3 2291.73  4765.9 2291.73  4773.8 2289.67  4776.9 2290.54  4780.0 2291.41
  4788.6 2289.78  4794.7 2290.68  4801.2 2288.66  4809.5 2287.54  4815.6 2287.88
  4824.2 2286.78  4830.3 2284.46  4845.1 2268.71  4851.2 2264.98  4859.8 2262.23
  4887.3 2258.60  4924.2 2257.67  4931.1 2255.79  4960.5 2255.61  4985.4 2250.45
  4985.7 2249.95  4989.7 2250.45  5001.5 2255.58  5010.0 2264.22  5017.7 2268.12
  5023.5 2267.60  5033.2 2268.91  5060.4 2269.38  5134.3 2275.59  5164.6 2276.55
#Mann=4,-1,0
  4761.3    0.07       0  4776.9    0.16       0  4985.4    0.07       0
  4989.7    0.16       0
Bank Sta=4985.4,4989.7
Exp/Cntr=0.3,0.1

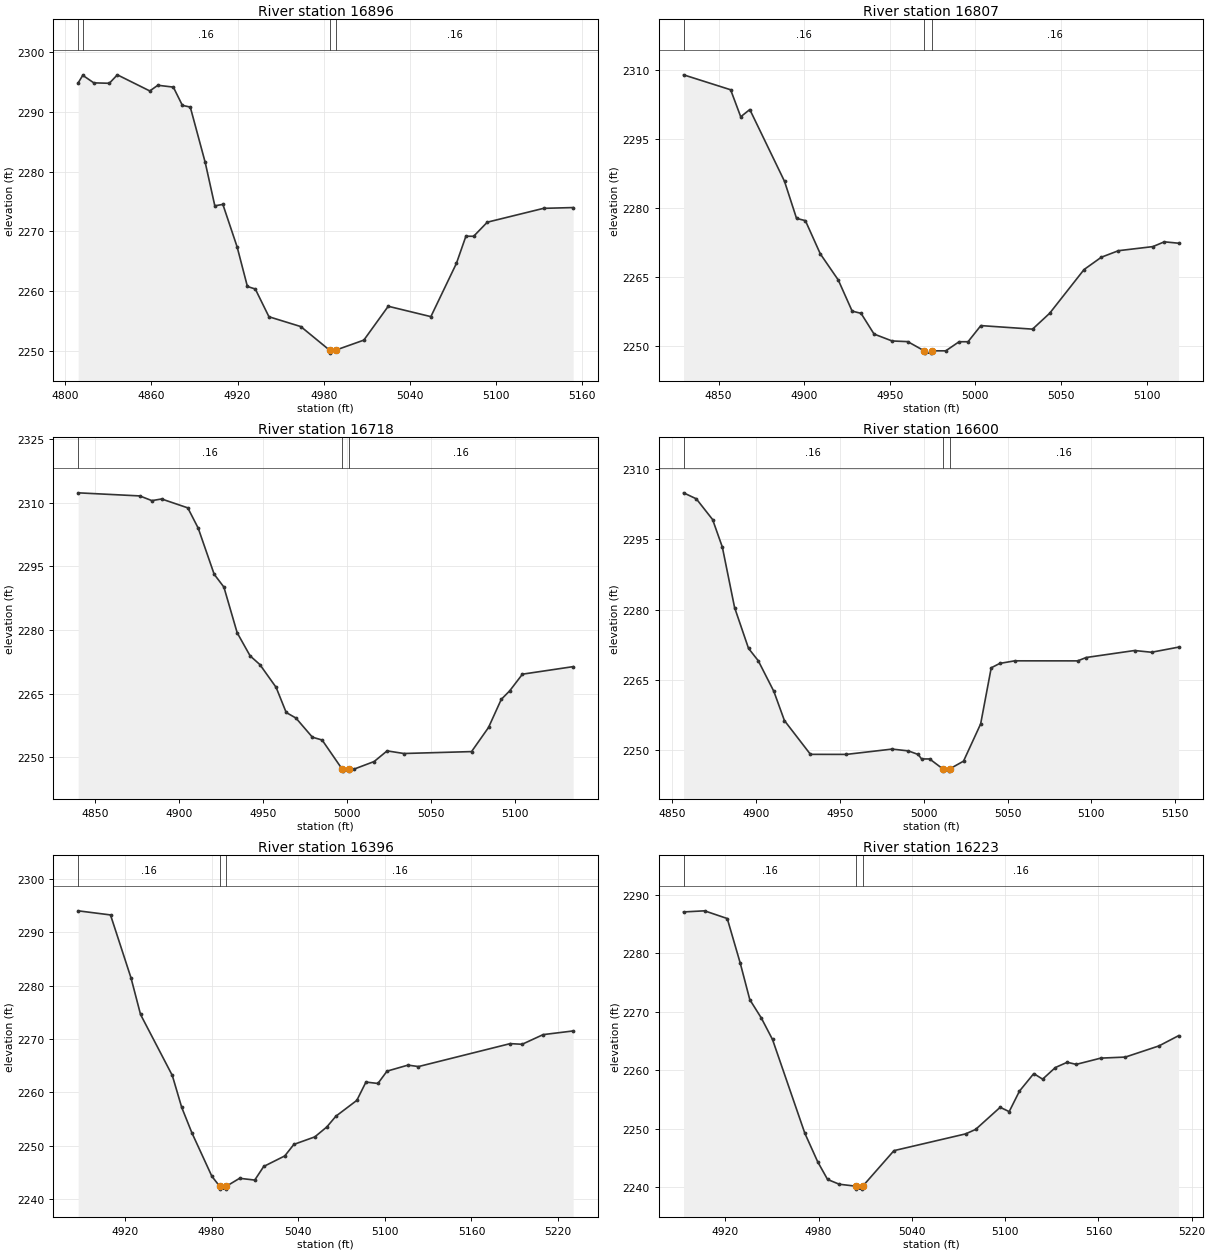
Type RM Length L Ch R = 1,16896,89,89,89
BEGIN DESCRIPTION:
Elm 52 16895.61
END DESCRIPTION:
XS GIS Cut Line= 3
      1510728.34      6765807.83      1510808.20      6765641.15
      1510867.02      6765492.38
#Sta/Elev= 30
  4809.0 2294.79  4812.2 2296.06  4819.9 2294.80  4830.7 2294.73  4836.3 2296.14
  4858.9 2293.45  4864.5 2294.40  4875.3 2294.09  4881.6 2291.04  4887.1 2290.76
  4897.5 2281.52  4904.2 2274.28  4909.8 2274.52  4919.7 2267.45  4926.9 2260.82
  4932.4 2260.40  4941.9 2255.77  4964.1 2254.13  4984.1 2250.20  4984.4 2249.70
  4988.4 2250.20  5008.0 2251.87  5025.0 2257.52  5054.7 2255.79  5072.5 2264.68
  5079.1 2269.21  5084.5 2269.20  5094.0 2271.55  5133.2 2273.86  5153.8 2273.99
#Mann=4,-1,0
  4809.0    0.07       0  4812.2    0.16       0  4984.1    0.07       0
  4988.4    0.16       0
Bank Sta=4984.1,4988.4
Exp/Cntr=0.3,0.1

Type RM Length L Ch R = 1,16807,89,89,89
BEGIN DESCRIPTION:
Elm 52 16806.53
END DESCRIPTION:
XS GIS Cut Line= 3
      1510849.88      6765804.31      1510898.48      6765648.09
      1510910.64      6765523.08
#Sta/Elev= 30
  4829.5 2309.05  4857.0 2305.80  4862.9 2299.92  4868.2 2301.50  4888.5 2285.86
  4895.5 2277.82  4900.7 2277.31  4909.4 2270.09  4919.9 2264.40  4928.0 2257.63
  4933.2 2257.15  4940.8 2252.64  4951.3 2251.14  4960.5 2250.99  4970.1 2248.99
  4970.4 2248.49  4974.1 2248.49  4974.4 2248.99  4982.7 2248.99  4990.5 2250.97
  4995.7 2250.97  5003.2 2254.48  5033.4 2253.71  5043.4 2257.16  5063.5 2266.68
  5073.6 2269.36  5083.6 2270.78  5103.7 2271.67  5110.4 2272.71  5118.7 2272.41
#Mann=3,-1,0
  4829.5    0.16       0  4970.1    0.07       0  4974.4    0.16       0
Bank Sta=4970.1,4974.4
Exp/Cntr=0.3,0.1

Type RM Length L Ch R = 1,16718,118,118,118
BEGIN DESCRIPTION:
Elm 52 16718.36
END DESCRIPTION:
XS GIS Cut Line= 3
      1511053.02      6765809.58      1510971.69      6765671.67
      1510955.00      6765538.01
#Sta/Elev= 30
  4839.9 2312.36  4876.6 2311.63  4883.8 2310.52  4889.6 2310.91  4905.2 2308.81
  4911.4 2304.02  4920.9 2293.15  4926.7 2290.11  4934.6 2279.34  4942.3 2273.89
  4948.1 2271.84  4957.8 2266.45  4963.8 2260.52  4969.6 2259.21  4979.4 2254.69
  4985.2 2254.02  4997.1 2247.18  4997.4 2246.68  5001.1 2246.68  5001.4 2247.18
  5004.4 2247.18  5016.2 2248.95  5023.9 2251.46  5033.9 2250.84  5074.2 2251.29
  5084.3 2256.98  5091.9 2263.62  5096.9 2265.62  5104.5 2269.56  5134.7 2271.34
#Mann=3,-1,0
  4839.9    0.16       0  4997.1    0.07       0  5001.4    0.16       0
Bank Sta=4997.1,5001.4
Exp/Cntr=0.3,0.1

Type RM Length L Ch R = 1,16600,204,204,204
BEGIN DESCRIPTION:
Elm 52 16599.97
END DESCRIPTION:
XS GIS Cut Line= 3
      1511131.14      6765714.10      1511058.20      6765592.53
      1511028.84      6765442.25
#Sta/Elev= 30
  4857.0 2304.93  4864.6 2303.65  4874.3 2299.23  4880.1 2293.36  4887.4 2280.46
  4895.7 2271.75  4901.5 2269.11  4910.8 2262.57  4917.1 2256.34  4932.6 2249.14
  4954.0 2249.13  4981.2 2250.26  4990.9 2249.88  4996.8 2249.11  4998.8 2248.16
  5003.6 2248.16  5011.4 2246.06  5011.7 2245.56  5015.4 2245.56  5015.7 2246.06
  5023.8 2247.69  5034.0 2255.63  5040.3 2267.60  5045.4 2268.54  5054.3 2269.09
  5091.8 2269.08  5096.9 2269.80  5125.7 2271.29  5135.8 2270.92  5151.9 2272.01
#Mann=3,-1,0
  4857.0    0.16       0  5011.4    0.07       0  5015.7    0.16       0
Bank Sta=5011.4,5015.7
Exp/Cntr=0.3,0.1

Type RM Length L Ch R = 1,16396,173,173,173
BEGIN DESCRIPTION:
Elm 52 16396.03
END DESCRIPTION:
XS GIS Cut Line= 3
      1511304.72      6765599.47      1511219.66      6765526.56
      1511080.38      6765342.57
#Sta/Elev= 30
  4887.6 2294.02  4910.0 2293.25  4924.2 2281.44  4930.8 2274.58  4952.8 2263.14
  4959.3 2257.16  4966.3 2252.42  4980.2 2244.23  4985.7 2242.32  4986.0 2241.82
  4989.7 2241.82  4990.0 2242.32  4999.4 2243.85  5009.9 2243.52  5016.1 2246.07
  5030.7 2248.05  5037.0 2250.21  5051.5 2251.62  5059.8 2253.48  5066.1 2255.50
  5080.6 2258.47  5086.9 2261.90  5095.2 2261.64  5101.5 2263.95  5116.0 2265.08
  5123.3 2264.81  5186.8 2269.11  5195.1 2268.99  5209.6 2270.80  5230.4 2271.49
#Mann=3,-1,0
  4887.6    0.16       0  4985.7    0.07       0  4990.0    0.16       0
Bank Sta=4985.7,4990
Exp/Cntr=0.3,0.1

Type RM Length L Ch R = 1,16223,165,165,165
BEGIN DESCRIPTION:
Elm 52 16222.829
END DESCRIPTION:
XS GIS Cut Line= 3
      1511404.97      6765487.96      1511340.68      6765402.68
      1511235.31      6765219.30
#Sta/Elev= 30
  4893.2 2287.08  4906.7 2287.27  4921.3 2285.95  4929.6 2278.36  4935.8 2272.06
  4943.2 2268.92  4950.4 2265.24  4971.2 2249.18  4979.5 2244.28  4985.8 2241.28
  4993.3 2240.46  5004.1 2240.12  5004.4 2239.62  5008.2 2239.62  5008.4 2240.12
  5028.5 2246.21  5074.6 2249.08  5081.0 2249.84  5096.8 2253.63  5102.6 2252.89
  5109.2 2256.40  5118.4 2259.40  5124.1 2258.45  5132.3 2260.44  5139.9 2261.34
  5145.7 2260.98  5161.5 2262.05  5177.3 2262.23  5198.9 2264.14  5211.5 2265.89
#Mann=3,-1,0
  4893.2    0.16       0  5004.1    0.07       0  5008.4    0.16       0
Bank Sta=5004.1,5008.4
Exp/Cntr=0.3,0.1

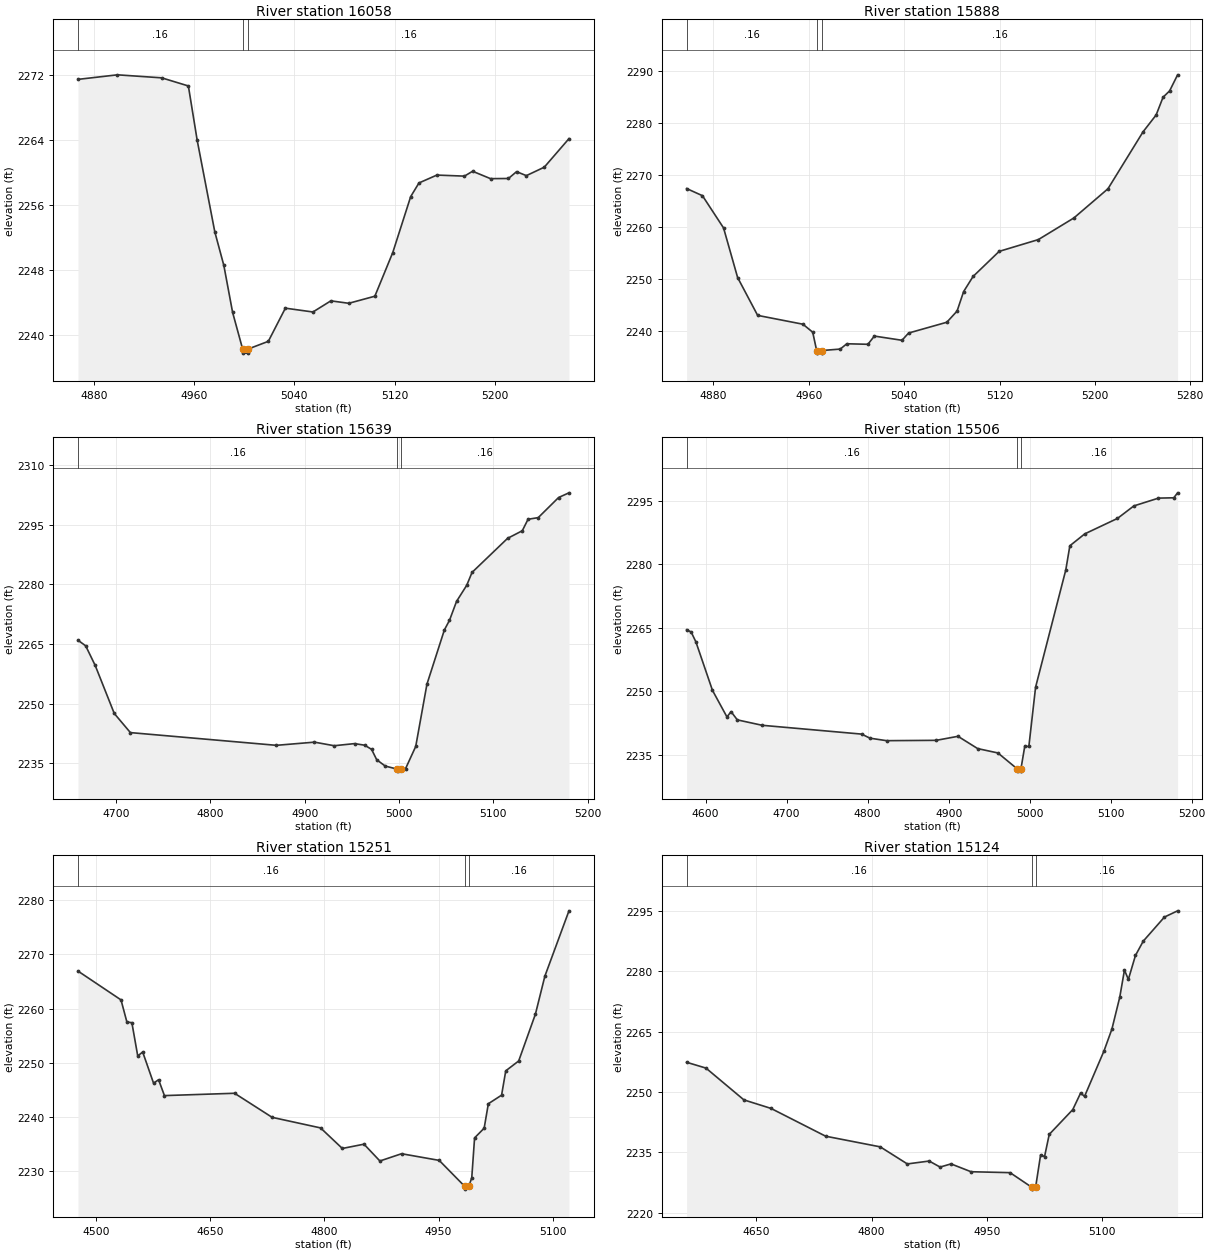
Type RM Length L Ch R = 1,16058,170,170,170
BEGIN DESCRIPTION:
Elm 52 16057.95
END DESCRIPTION:
XS GIS Cut Line= 3
      1511553.00      6765394.62      1511455.77      6765300.87
      1511289.55      6765105.21
#Sta/Elev= 30
  4867.4 2271.42  4898.9 2271.98  4934.2 2271.61  4955.5 2270.61  4962.5 2263.96
  4976.6 2252.66  4983.8 2248.54  4990.8 2242.76  4998.8 2238.25  4999.0 2237.75
  5002.8 2237.75  5003.1 2238.25  5019.3 2239.20  5032.9 2243.28  5054.9 2242.81
  5069.2 2244.18  5083.5 2243.88  5104.3 2244.75  5118.6 2250.12  5132.9 2257.00
  5139.5 2258.68  5153.8 2259.65  5175.8 2259.52  5182.3 2260.12  5196.6 2259.21
  5210.9 2259.23  5217.4 2260.07  5225.2 2259.58  5239.5 2260.62  5259.2 2264.13
#Mann=3,-1,0
  4867.4    0.16       0  4998.8    0.07       0  5003.1    0.16       0
Bank Sta=4998.8,5003.1
Exp/Cntr=0.3,0.1

Type RM Length L Ch R = 1,15888,249,249,249
BEGIN DESCRIPTION:
Elm 52 15887.92
END DESCRIPTION:
XS GIS Cut Line= 2
      1511594.66      6765286.98      1511425.13      6764911.59
#Sta/Elev= 30
  4857.5 2267.40  4870.8 2266.02  4888.5 2259.82  4900.3 2250.28  4917.1 2243.00
  4955.1 2241.30  4963.3 2239.76  4966.6 2236.24  4966.9 2235.74  4970.7 2235.74
  4971.0 2236.24  4986.4 2236.52  4991.9 2237.54  5009.6 2237.44  5015.0 2239.02
  5038.2 2238.21  5043.7 2239.60  5075.8 2241.68  5084.4 2243.83  5089.9 2247.58
  5097.8 2250.48  5119.7 2255.31  5152.6 2257.58  5182.4 2261.74  5211.0 2267.36
  5240.4 2278.30  5251.4 2281.55  5257.2 2284.96  5262.7 2286.18  5269.4 2289.27
#Mann=3,-1,0
  4857.5    0.16       0  4966.6    0.07       0  4971.0    0.16       0
Bank Sta=4966.6,4971
Exp/Cntr=0.3,0.1

Type RM Length L Ch R = 1,15639,133,133,133
BEGIN DESCRIPTION:
Elm 52 15639.18
END DESCRIPTION:
XS GIS Cut Line= 3
      1511601.61      6765266.11      1511639.80      6765007.47
      1511540.83      6764767.85
#Sta/Elev= 30
  4659.6 2265.97  4667.8 2264.55  4677.9 2259.61  4698.1 2247.54  4715.2 2242.73
  4870.0 2239.53  4910.4 2240.33  4931.3 2239.43  4952.9 2239.96  4963.7 2239.56
  4971.0 2238.51  4976.4 2235.91  4985.4 2234.32  4998.2 2233.54  4998.5 2233.04
  5002.6 2233.54  5007.0 2233.66  5017.8 2239.25  5029.7 2254.92  5048.2 2268.57
  5053.6 2270.97  5061.1 2275.74  5071.9 2279.79  5077.5 2283.02  5115.2 2291.59
  5130.8 2293.50  5136.9 2296.39  5147.7 2296.80  5169.3 2301.86  5180.3 2303.04
#Mann=3,-1,0
  4659.6    0.16       0  4998.2    0.07       0  5002.6    0.16       0
Bank Sta=4998.2,5002.6
Exp/Cntr=0.3,0.1

Type RM Length L Ch R = 1,15506,255,255,255
BEGIN DESCRIPTION:
Elm 52 15505.76
END DESCRIPTION:
XS GIS Cut Line= 3
      1511618.97      6765259.20      1511707.51      6764849.48
      1511679.87      6764664.62
#Sta/Elev= 30
  4576.5 2264.51  4582.1 2263.98  4588.0 2261.63  4608.4 2250.21  4626.3 2243.93
  4631.4 2245.17  4639.1 2243.23  4669.8 2241.95  4792.6 2239.87  4802.8 2238.91
  4823.3 2238.32  4884.7 2238.40  4911.5 2239.35  4935.8 2236.45  4960.8 2235.42
  4984.8 2231.63  4985.1 2231.13  4988.9 2231.13  4989.2 2231.63  4993.9 2236.96
  4999.0 2236.96  5007.3 2250.95  5044.6 2278.64  5049.6 2284.33  5068.0 2287.14
  5108.4 2290.79  5128.6 2293.74  5159.0 2295.58  5177.9 2295.66  5182.6 2296.83
#Mann=3,-1,0
  4576.5    0.16       0  4984.8    0.07       0  4989.2    0.16       0
Bank Sta=4984.8,4989.2
Exp/Cntr=0.3,0.1

Type RM Length L Ch R = 1,15251,127,127,127
BEGIN DESCRIPTION:
Elm 52 15250.64
END DESCRIPTION:
XS GIS Cut Line= 3
      1511604.98      6765288.02      1511944.74      6764888.97
      1512055.03      6764837.99
#Sta/Elev= 30
  4475.9 2266.91  4532.5 2261.59  4540.2 2257.53  4546.8 2257.38  4554.5 2251.25
  4561.0 2251.98  4575.3 2246.23  4581.9 2246.87  4589.6 2243.94  4681.8 2244.37
  4731.2 2239.93  4794.9 2237.98  4823.5 2234.19  4852.0 2234.98  4872.9 2231.88
  4901.4 2233.22  4950.9 2231.99  4984.5 2227.19  4984.9 2226.69  4989.8 2227.19
  4993.7 2228.79  4997.4 2236.14  5010.0 2237.93  5015.5 2242.44  5032.9 2244.02
  5038.4 2248.51  5055.4 2250.33  5077.4 2258.97  5089.8 2265.96  5121.5 2278.02
#Mann=3,-1,0
  4475.9    0.16       0  4984.5    0.07       0  4989.8    0.16       0
Bank Sta=4984.5,4989.8
Exp/Cntr=0.3,0.1

Type RM Length L Ch R = 1,15124,211,211,211
BEGIN DESCRIPTION:
Elm 52 15124.29
END DESCRIPTION:
XS GIS Cut Line= 3
      1511690.13      6765278.32      1511936.68      6765000.52
      1512198.86      6764950.17
#Sta/Elev= 30
  4559.4 2257.40  4584.6 2255.95  4633.9 2248.04  4669.1 2245.92  4740.2 2239.00
  4811.2 2236.35  4846.4 2232.10  4874.8 2232.82  4889.0 2231.32  4903.2 2232.11
  4929.2 2230.16  4980.0 2229.93  5007.9 2226.33  5008.3 2225.83  5013.2 2226.33
  5019.7 2234.38  5024.8 2233.91  5030.9 2239.45  5061.5 2245.62  5071.7 2249.74
  5076.8 2248.91  5102.2 2260.27  5112.4 2265.67  5122.6 2273.60  5128.7 2280.34
  5133.8 2278.03  5143.0 2283.98  5153.1 2287.53  5180.7 2293.54  5197.8 2295.09
#Mann=3,-1,0
  4559.4    0.16       0  5007.9    0.07       0  5013.2    0.16       0
Bank Sta=5007.9,5013.2
Exp/Cntr=0.3,0.1

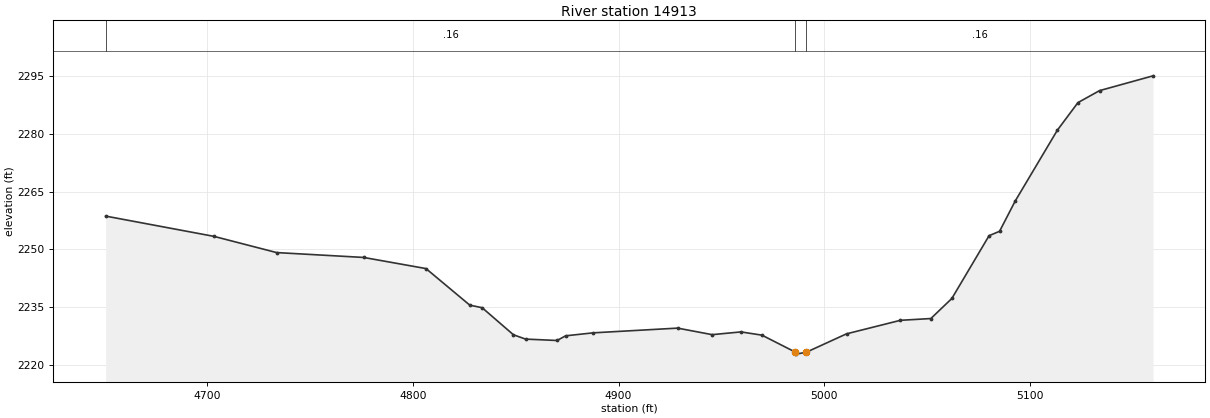
Type RM Length L Ch R = 1,14913,121,121,121
BEGIN DESCRIPTION:
Elm 52 14913.12
END DESCRIPTION:
XS GIS Cut Line= 3
      1511693.63      6765319.96      1511884.59      6765198.44
      1512160.36      6765136.00
#Sta/Elev= 30
  4650.7 2258.64  4703.3 2253.40  4733.8 2249.20  4776.1 2247.94  4806.4 2245.06
  4827.7 2235.59  4833.7 2234.93  4848.9 2227.93  4854.8 2226.81  4870.1 2226.45
  4874.3 2227.66  4887.7 2228.43  4928.7 2229.65  4945.5 2227.96  4959.5 2228.67
  4969.7 2227.83  4986.0 2223.42  4986.4 2222.92  4991.3 2223.42  5010.8 2228.17
  5037.0 2231.67  5051.8 2232.13  5062.0 2237.32  5080.1 2253.57  5085.2 2254.71
  5092.8 2262.54  5113.3 2280.88  5123.3 2288.01  5133.8 2291.11  5159.8 2294.94
#Mann=3,-1,0
  4650.7    0.16       0  4986.0    0.07       0  4991.3    0.16       0
Bank Sta=4986,4991.3
Exp/Cntr=0.3,0.1