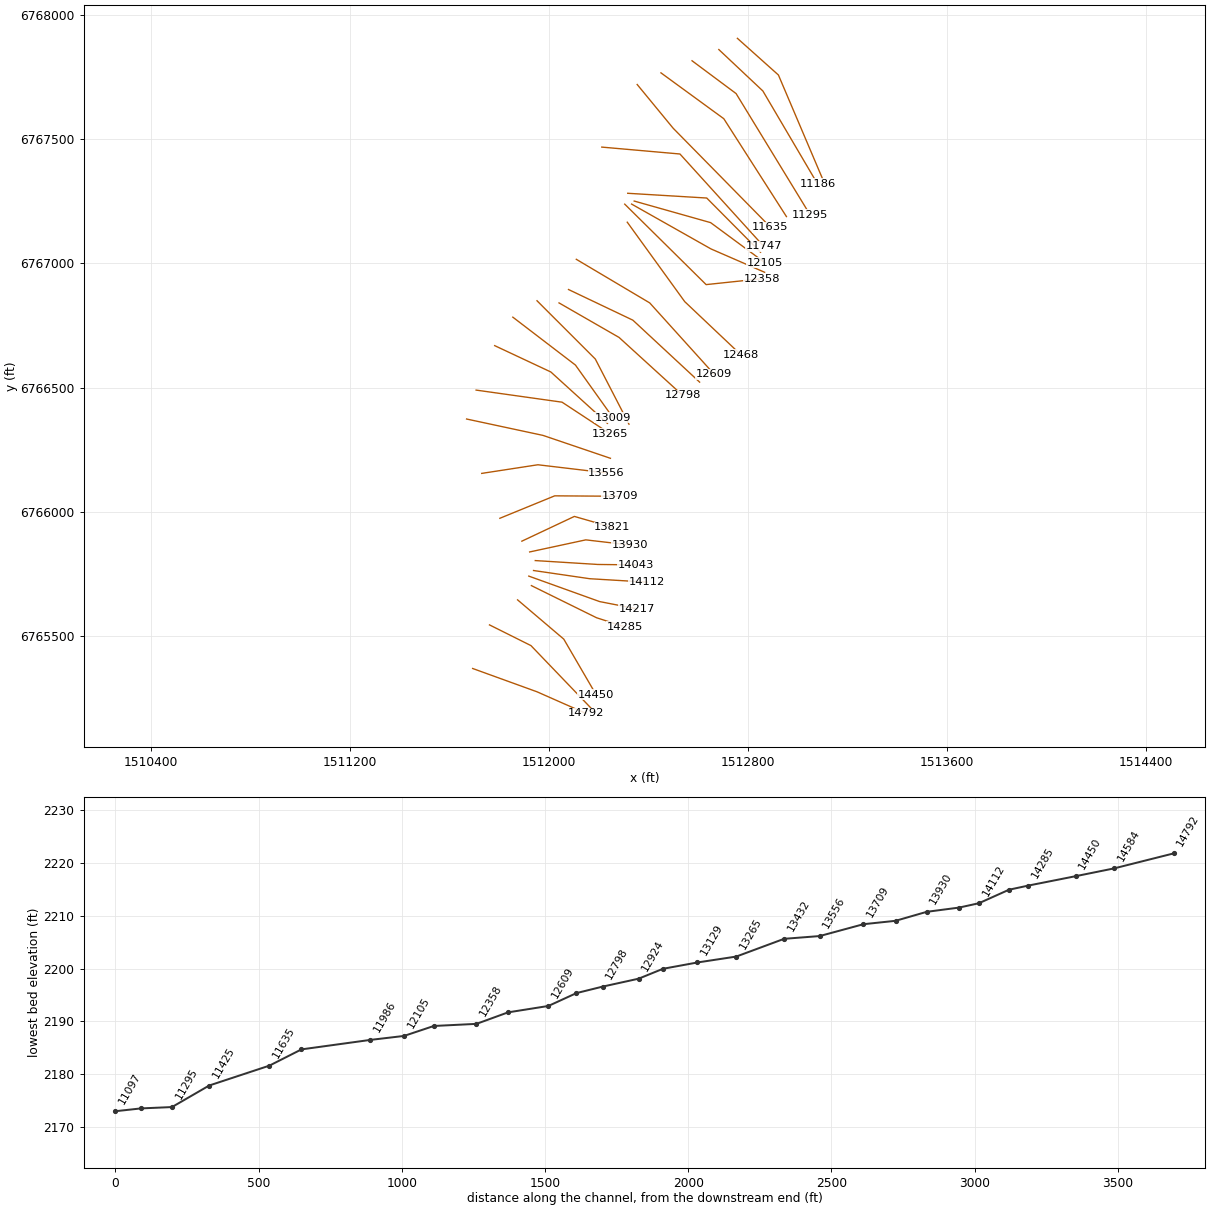
HEC-RAS study Elm 52.prj: Elm 52 Base Level Engineering

--- Elm 52.g01 (geometry) --- (continued)

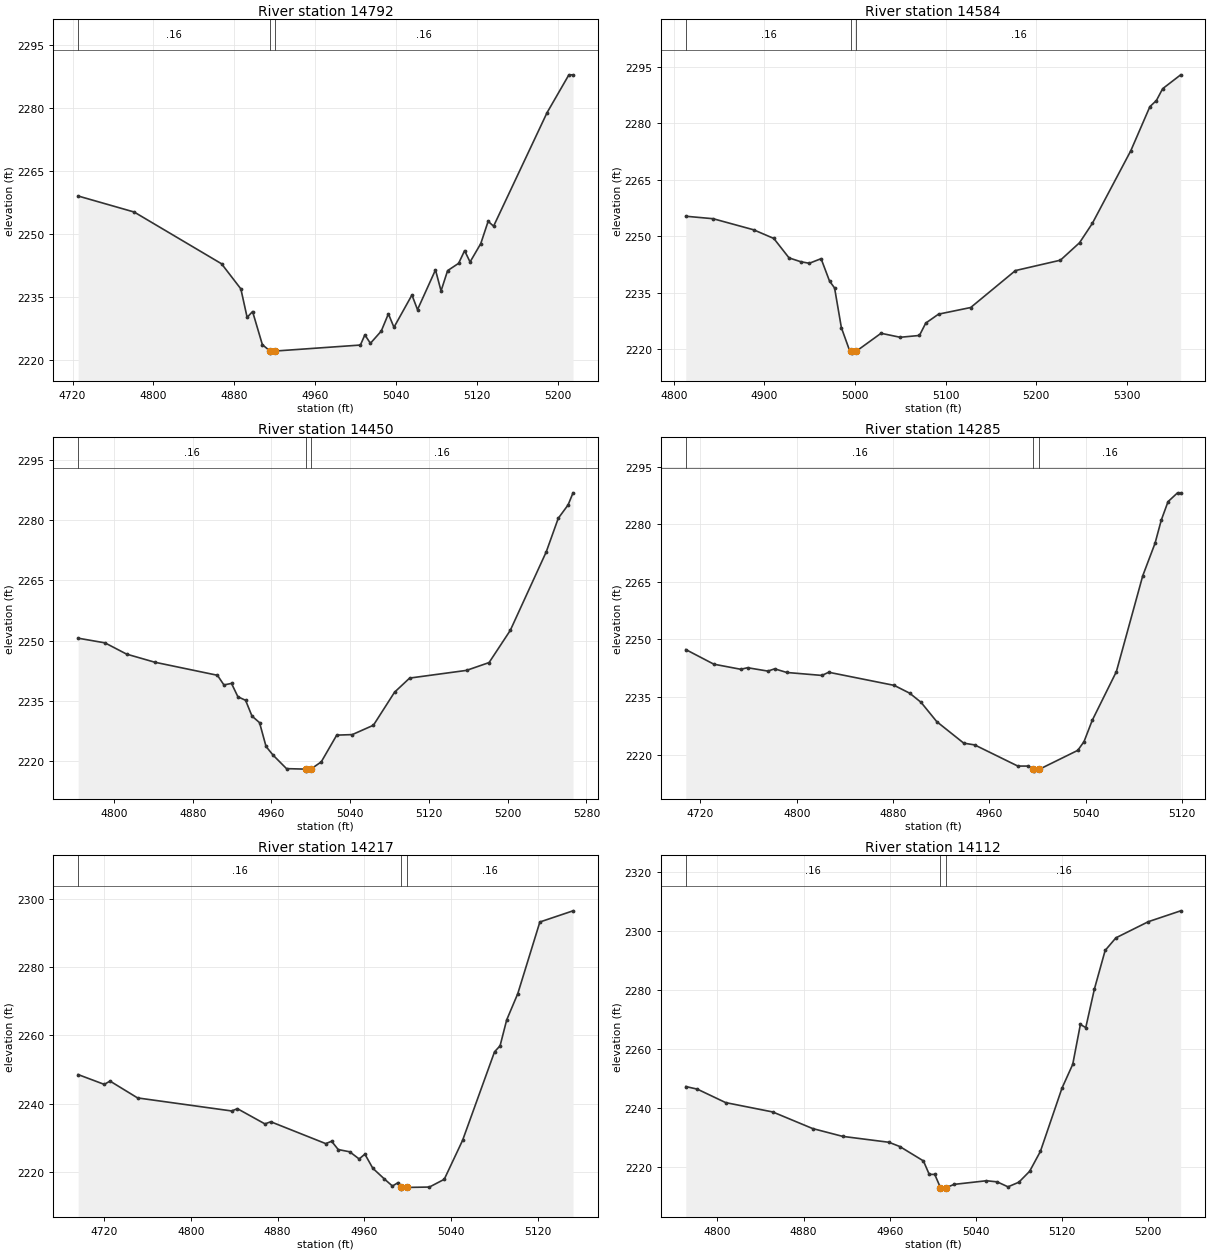
Type RM Length L Ch R = 1,14792,208,208,208
BEGIN DESCRIPTION:
Elm 52 14791.7
END DESCRIPTION:
XS GIS Cut Line= 3
      1511693.64      6765370.31      1511952.30      6765276.56
      1512148.53      6765189.74
#Sta/Elev= 30
  4725.6 2259.04  4781.0 2255.24  4867.5 2242.95  4886.6 2236.99  4892.8 2230.23
  4898.2 2231.61  4907.9 2223.74  4915.5 2222.24  4915.9 2221.74  4920.8 2222.24
  5004.9 2223.66  5009.3 2226.07  5014.8 2224.07  5025.5 2226.96  5032.6 2231.07
  5038.1 2227.87  5055.9 2235.54  5061.4 2232.06  5079.2 2241.50  5084.7 2236.51
  5091.2 2241.33  5102.1 2243.06  5108.0 2246.07  5113.4 2243.38  5124.0 2247.74
  5131.3 2253.03  5136.7 2251.88  5189.6 2278.83  5211.2 2287.81  5215.3 2287.81
#Mann=3,-1,0
  4725.6    0.16       0  4915.5    0.07       0  4920.8    0.16       0
Bank Sta=4915.5,4920.8
Exp/Cntr=0.3,0.1

Type RM Length L Ch R = 1,14584,134,134,134
BEGIN DESCRIPTION:
Elm 52 14584.49
END DESCRIPTION:
XS GIS Cut Line= 3
      1511761.36      6765545.65      1511928.00      6765462.33
      1512177.44      6765202.49
#Sta/Elev= 30
  4813.1 2255.26  4843.3 2254.60  4888.0 2251.66  4910.3 2249.36  4927.1 2244.20
  4940.2 2243.17  4949.5 2242.77  4962.5 2243.99  4971.8 2238.06  4977.4 2236.21
  4984.9 2225.68  4994.2 2219.45  4996.0 2219.41  4996.4 2218.91  5001.3 2219.41
  5028.7 2224.18  5049.8 2223.12  5071.1 2223.60  5078.1 2226.89  5092.2 2229.26
  5127.7 2231.02  5177.1 2240.83  5226.8 2243.59  5247.9 2248.22  5262.0 2253.34
  5304.5 2272.64  5325.6 2284.36  5332.8 2285.99  5339.7 2289.13  5359.6 2292.81
#Mann=3,-1,0
  4813.1    0.16       0  4996.0    0.07       0  5001.3    0.16       0
Bank Sta=4996,5001.3
Exp/Cntr=0.3,0.1

Type RM Length L Ch R = 1,14450,165,165,165
BEGIN DESCRIPTION:
Elm 52 14449.53
END DESCRIPTION:
XS GIS Cut Line= 3
      1511874.19      6765646.34      1512059.94      6765488.37
      1512190.10      6765264.49
#Sta/Elev= 30
  4763.6 2250.60  4790.9 2249.43  4812.8 2246.63  4841.4 2244.61  4905.1 2241.35
  4911.7 2238.94  4919.4 2239.32  4925.9 2235.99  4933.7 2235.11  4940.2 2231.18
  4947.9 2229.53  4954.5 2223.59  4961.6 2221.44  4975.3 2218.06  4994.7 2217.94
  4995.1 2217.44  5000.0 2217.94  5010.6 2219.75  5026.3 2226.42  5042.1 2226.55
  5063.6 2228.89  5085.1 2237.14  5100.4 2240.65  5158.2 2242.57  5181.1 2244.52
  5202.6 2252.53  5239.2 2272.14  5251.4 2280.51  5261.4 2283.85  5266.4 2286.86
#Mann=3,-1,0
  4763.6    0.16       0  4994.7    0.07       0  5000.0    0.16       0
Bank Sta=4994.7,5000
Exp/Cntr=0.3,0.1

Type RM Length L Ch R = 1,14285,68,68,68
BEGIN DESCRIPTION:
Elm 52 14285.288
END DESCRIPTION:
XS GIS Cut Line= 3
      1511929.77      6765703.63      1512191.81      6765574.34
      1512305.02      6765537.99
#Sta/Elev= 30
  4707.8 2247.35  4731.1 2243.54  4753.5 2242.21  4759.1 2242.62  4776.0 2241.74
  4781.6 2242.33  4791.7 2241.38  4820.9 2240.61  4826.5 2241.44  4880.9 2238.02
  4893.8 2235.98  4903.2 2233.61  4916.3 2228.56  4938.7 2222.96  4947.8 2222.50
  4983.6 2216.99  4992.4 2216.99  4996.3 2216.17  4996.7 2215.67  5001.6 2216.17
  5033.4 2221.08  5038.6 2223.35  5045.4 2228.88  5065.5 2241.61  5087.4 2266.59
  5097.6 2275.05  5102.8 2281.10  5108.4 2285.90  5116.3 2288.20  5118.9 2288.20
#Mann=3,-1,0
  4707.8    0.16       0  4996.3    0.07       0  5001.6    0.16       0
Bank Sta=4996.3,5001.6
Exp/Cntr=0.3,0.1

Type RM Length L Ch R = 1,14217,105,105,105
BEGIN DESCRIPTION:
Elm 52 14217.18
END DESCRIPTION:
XS GIS Cut Line= 3
      1511919.27      6765741.86      1512204.04      6765639.41
      1512355.05      6765609.90
#Sta/Elev= 30
  4696.1 2248.51  4720.2 2245.63  4725.5 2246.60  4750.9 2241.66  4837.7 2237.83
  4843.0 2238.50  4868.4 2234.03  4873.8 2234.66  4924.5 2228.24  4929.9 2228.94
  4936.0 2226.50  4946.6 2225.84  4955.3 2223.74  4960.6 2225.15  4967.9 2221.01
  4978.5 2217.88  4986.0 2215.79  4991.3 2216.80  4993.9 2215.38  4994.3 2214.88
  4999.2 2215.38  5020.1 2215.49  5033.8 2217.76  5050.7 2229.19  5080.2 2255.20
  5085.3 2256.96  5091.4 2264.56  5101.6 2272.25  5122.0 2293.31  5152.6 2296.59
#Mann=3,-1,0
  4696.1    0.16       0  4993.9    0.07       0  4999.2    0.16       0
Bank Sta=4993.9,4999.2
Exp/Cntr=0.3,0.1

Type RM Length L Ch R = 1,14112,69,69,69
BEGIN DESCRIPTION:
Elm 52 14111.89
END DESCRIPTION:
XS GIS Cut Line= 3
      1511938.39      6765764.41      1512164.11      6765731.42
      1512394.98      6765717.54
#Sta/Elev= 30
  4770.6 2247.21  4781.3 2246.33  4807.6 2241.75  4851.3 2238.57  4888.4 2232.92
  4916.2 2230.27  4959.2 2228.26  4969.3 2226.81  4991.2 2221.92  4996.6 2217.34
  5001.7 2217.34  5007.0 2212.83  5007.4 2212.33  5012.3 2212.83  5019.6 2213.94
  5049.7 2215.18  5059.7 2214.80  5069.7 2213.11  5079.8 2214.69  5089.8 2218.40
  5099.8 2225.18  5119.8 2246.65  5129.8 2254.77  5136.9 2268.32  5141.9 2267.26
  5149.9 2280.35  5159.9 2293.50  5169.9 2297.78  5200.0 2303.27  5230.0 2306.96
#Mann=3,-1,0
  4770.6    0.16       0  5007.0    0.07       0  5012.3    0.16       0
Bank Sta=5007,5012.3
Exp/Cntr=0.3,0.1

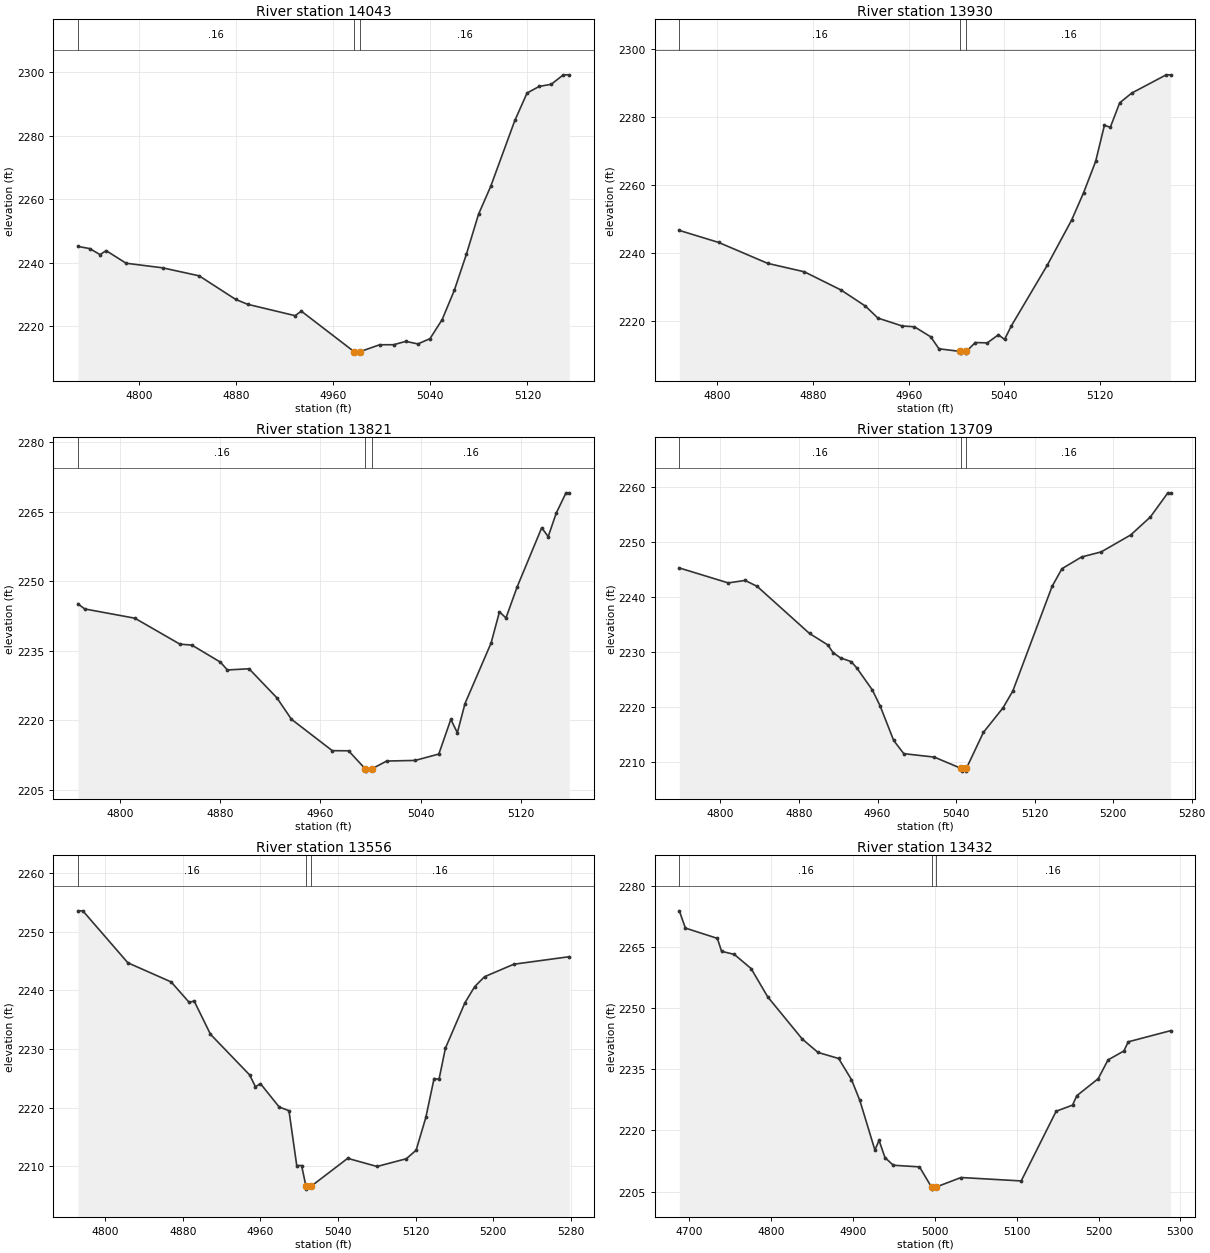
Type RM Length L Ch R = 1,14043,113,113,113
BEGIN DESCRIPTION:
Elm 52 14042.65
END DESCRIPTION:
XS GIS Cut Line= 3
      1511945.33      6765804.34      1512197.09      6765788.72
      1512349.83      6765786.98
#Sta/Elev= 30
  4749.5 2245.15  4759.2 2244.47  4767.7 2242.57  4772.7 2243.82  4789.2 2239.85
  4819.3 2238.40  4849.4 2235.88  4879.4 2228.47  4889.4 2226.90  4928.5 2223.32
  4933.6 2224.75  4977.0 2212.01  4977.4 2211.51  4982.3 2212.01  4998.2 2214.15
  5009.7 2214.16  5019.7 2215.22  5029.7 2214.41  5039.7 2216.07  5049.7 2222.08
  5059.7 2231.27  5069.7 2242.70  5079.7 2255.30  5089.7 2264.05  5109.7 2284.93
  5119.7 2293.51  5129.7 2295.59  5139.7 2296.28  5149.6 2299.25  5154.5 2299.25
#Mann=3,-1,0
  4749.5    0.16       0  4977.0    0.07       0  4982.3    0.16       0
Bank Sta=4977,4982.3
Exp/Cntr=0.3,0.1

Type RM Length L Ch R = 1,13930,109,109,109
BEGIN DESCRIPTION:
Elm 52 13930.28
END DESCRIPTION:
XS GIS Cut Line= 3
      1511922.77      6765839.06      1512148.48      6765887.67
      1512327.29      6765866.84
#Sta/Elev= 30
  4768.1 2246.73  4801.1 2243.19  4842.0 2237.06  4872.7 2234.58  4903.4 2229.23
  4923.8 2224.50  4934.2 2221.00  4954.5 2218.68  4964.7 2218.45  4978.4 2215.49
  4985.2 2211.99  5002.9 2211.21  5003.3 2210.71  5007.8 2210.71  5008.2 2211.21
  5015.6 2213.82  5025.7 2213.72  5035.0 2216.11  5040.1 2214.72  5045.8 2218.72
  5076.0 2236.62  5096.2 2249.76  5106.2 2257.78  5116.3 2266.99  5123.6 2277.54
  5128.6 2277.03  5136.4 2284.18  5146.5 2287.05  5175.3 2292.40  5179.0 2292.40
#Mann=3,-1,0
  4768.1    0.16       0  5002.9    0.07       0  5008.2    0.16       0
Bank Sta=5002.9,5008.2
Exp/Cntr=0.3,0.1

Type RM Length L Ch R = 1,13821,112,112,112
BEGIN DESCRIPTION:
Elm 52 13821.371
END DESCRIPTION:
XS GIS Cut Line= 3
      1511891.49      6765882.44      1512102.50      6765981.96
      1512254.99      6765938.00
#Sta/Elev= 30
  4766.7 2245.13  4772.1 2244.04  4812.1 2242.04  4848.0 2236.44  4857.6 2236.23
  4880.4 2232.54  4885.9 2230.86  4903.2 2231.12  4925.4 2224.85  4937.0 2220.22
  4969.6 2213.43  4982.6 2213.40  4995.9 2209.51  4996.4 2209.01  5001.3 2209.51
  5013.0 2211.19  5035.7 2211.32  5054.6 2212.70  5064.2 2220.19  5069.4 2217.30
  5075.5 2223.60  5096.3 2236.67  5103.0 2243.41  5108.2 2242.10  5117.1 2248.79
  5136.7 2261.57  5141.9 2259.67  5148.3 2264.74  5156.1 2269.12  5158.7 2269.12
#Mann=3,-1,0
  4766.7    0.16       0  4995.9    0.07       0  5001.3    0.16       0
Bank Sta=4995.9,5001.3
Exp/Cntr=0.3,0.1

Type RM Length L Ch R = 1,13709,153,153,153
BEGIN DESCRIPTION:
Elm 52 13708.76
END DESCRIPTION:
XS GIS Cut Line= 3
      1511803.02      6765974.49      1512023.48      6766064.76
      1512285.65      6766063.02
#Sta/Elev= 30
  4758.1 2245.34  4807.9 2242.62  4825.1 2243.07  4837.3 2242.00  4890.7 2233.42
  4909.3 2231.34  4914.7 2229.93  4922.3 2228.97  4933.1 2228.30  4938.7 2227.18
  4954.7 2223.14  4962.7 2220.21  4976.4 2213.96  4986.7 2211.55  5017.8 2210.92
  5045.1 2208.87  5045.6 2208.37  5050.1 2208.37  5050.5 2208.87  5067.8 2215.42
  5087.8 2219.89  5097.8 2222.96  5137.8 2242.00  5147.8 2245.20  5167.8 2247.34
  5187.8 2248.26  5217.9 2251.35  5237.9 2254.62  5255.7 2259.01  5258.5 2259.01
#Mann=3,-1,0
  4758.1    0.16       0  5045.1    0.07       0  5050.5    0.16       0
Bank Sta=5045.1,5050.5
Exp/Cntr=0.3,0.1

Type RM Length L Ch R = 1,13556,124,124,124
BEGIN DESCRIPTION:
Elm 52 13556.47
END DESCRIPTION:
XS GIS Cut Line= 3
      1511730.12      6766155.04      1511955.77      6766189.76
      1512231.73      6766156.99
#Sta/Elev= 30
  4772.0 2253.57  4777.0 2253.57  4823.4 2244.71  4868.0 2241.45  4886.6 2237.96
  4891.7 2238.20  4908.5 2232.53  4948.9 2225.59  4954.9 2223.57  4960.0 2224.12
  4979.3 2220.13  4989.4 2219.50  4997.4 2210.15  5002.4 2210.15  5006.9 2206.63
  5007.3 2206.13  5012.3 2206.63  5049.9 2211.38  5080.1 2209.99  5110.3 2211.31
  5120.4 2212.76  5130.4 2218.34  5138.9 2224.98  5144.0 2224.85  5150.6 2230.16
  5170.7 2237.90  5180.8 2240.66  5190.9 2242.34  5221.1 2244.47  5278.2 2245.75
#Mann=3,-1,0
  4772.0    0.16       0  5006.9    0.07       0  5012.3    0.16       0
Bank Sta=5006.9,5012.3
Exp/Cntr=0.3,0.1

Type RM Length L Ch R = 1,13432,167,167,167
BEGIN DESCRIPTION:
Elm 52 13432.3
END DESCRIPTION:
XS GIS Cut Line= 3
      1511669.28      6766373.79      1511976.61      6766307.81
      1512247.47      6766215.79
#Sta/Elev= 30
  4687.6 2273.89  4695.0 2269.66  4734.1 2267.13  4739.2 2263.96  4754.8 2263.20
  4775.3 2259.73  4795.7 2252.76  4838.0 2242.40  4857.1 2239.15  4882.3 2237.66
  4898.0 2232.48  4908.2 2227.37  4926.6 2215.20  4931.7 2217.57  4938.9 2213.35
  4949.1 2211.47  4981.1 2211.07  4995.8 2206.11  4996.2 2205.61  5001.2 2206.11
  5031.9 2208.46  5105.4 2207.62  5148.1 2224.72  5168.1 2226.22  5173.4 2228.54
  5199.5 2232.71  5211.5 2237.31  5230.9 2239.51  5236.2 2241.75  5288.0 2244.49
#Mann=3,-1,0
  4687.6    0.16       0  4995.8    0.07       0  5001.2    0.16       0
Bank Sta=4995.8,5001.2
Exp/Cntr=0.3,0.1

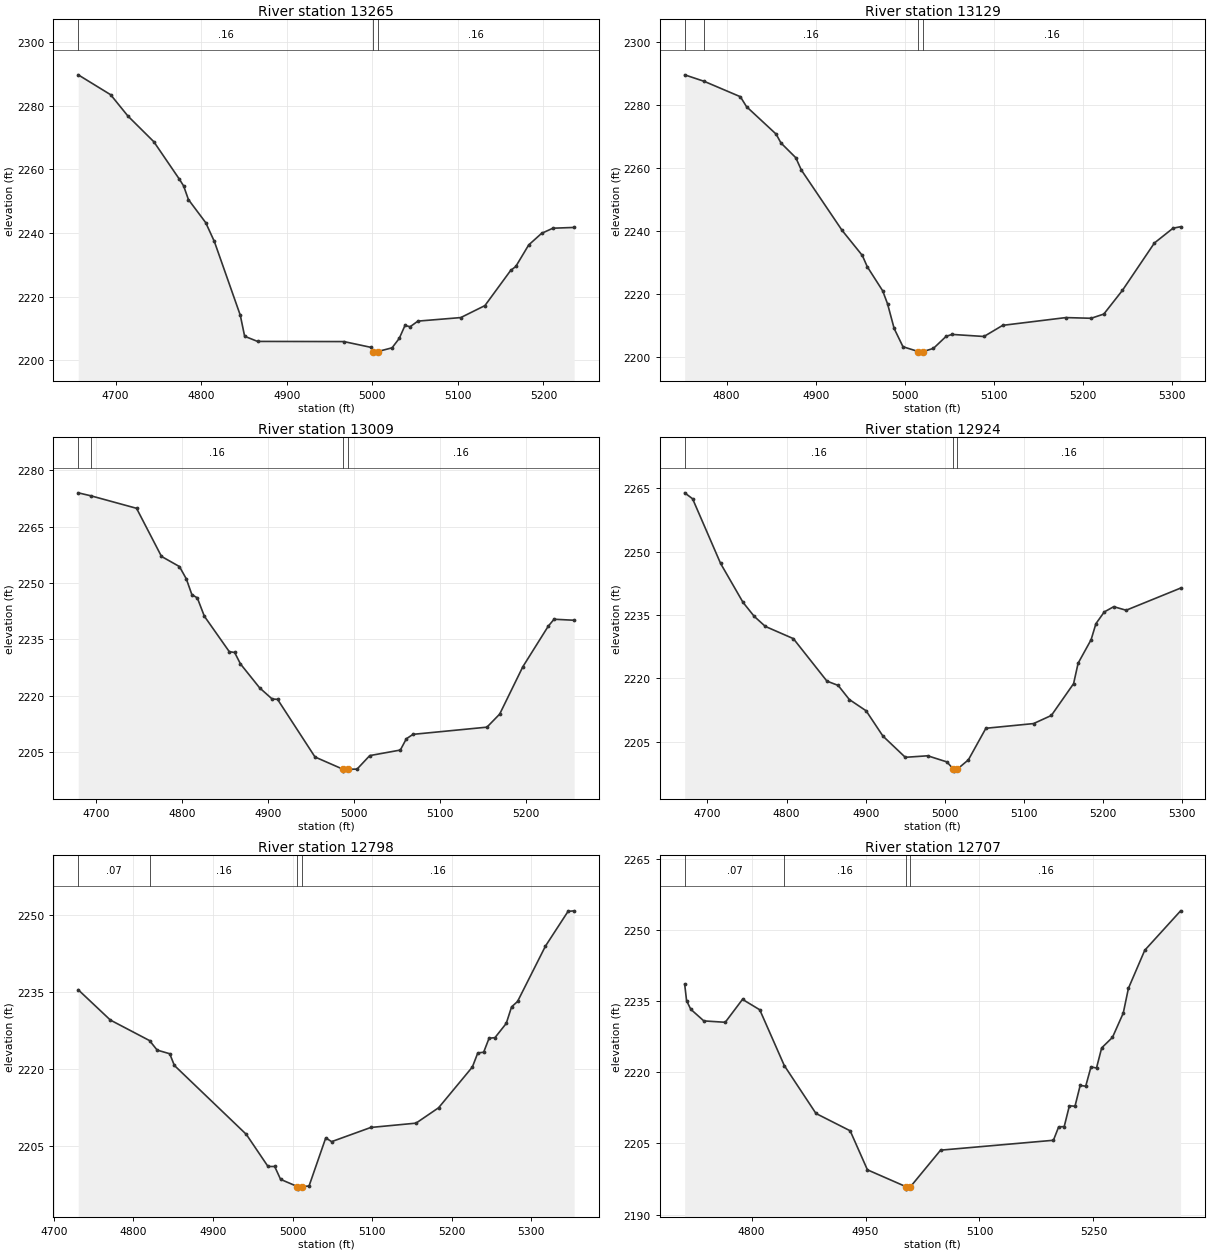
Type RM Length L Ch R = 1,13265,136,136,136
BEGIN DESCRIPTION:
Elm 52 13265.39
END DESCRIPTION:
XS GIS Cut Line= 3
      1511707.49      6766490.11      1512053.00      6766441.49
      1512245.74      6766314.73
#Sta/Elev= 30
  4656.3 2289.70  4694.2 2283.45  4714.4 2276.75  4744.7 2268.67  4774.5 2256.92
  4779.5 2254.79  4785.1 2250.51  4805.3 2243.26  4815.4 2237.34  4845.7 2214.18
  4850.8 2207.56  4865.9 2205.94  4966.8 2205.89  4998.3 2204.08  5001.0 2202.76
  5001.4 2202.26  5006.4 2202.76  5023.1 2203.93  5031.5 2206.89  5038.2 2210.95
  5044.2 2210.55  5053.3 2212.32  5103.4 2213.43  5131.6 2217.19  5161.7 2228.24
  5167.7 2229.49  5182.8 2236.26  5197.9 2239.90  5211.1 2241.51  5235.9 2241.75
#Mann=3,-1,0
  4656.3    0.16       0  5001.0    0.07       0  5006.4    0.16       0
Bank Sta=5001,5006.4
Exp/Cntr=0.3,0.1

Type RM Length L Ch R = 1,13129,120,120,120
BEGIN DESCRIPTION:
Elm 52 13129.07
END DESCRIPTION:
XS GIS Cut Line= 3
      1511782.15      6766668.93      1512007.86      6766563.02
      1512235.31      6766356.41
#Sta/Elev= 30
  4752.9 2289.62  4774.8 2287.55  4815.4 2282.66  4822.3 2279.50  4855.5 2270.78
  4861.0 2267.95  4877.6 2263.27  4883.8 2259.37  4929.5 2240.19  4952.3 2232.18
  4957.8 2228.62  4975.1 2220.96  4980.6 2216.80  4988.0 2208.97  4997.9 2203.17
  5015.2 2201.64  5015.6 2201.14  5020.6 2201.64  5032.1 2202.65  5046.3 2206.47
  5053.0 2207.09  5088.8 2206.43  5109.8 2209.97  5180.7 2212.44  5209.1 2212.22
  5223.3 2213.56  5244.2 2221.10  5280.1 2236.16  5301.0 2240.86  5309.5 2241.33
#Mann=4,-1,0
  4752.9    0.07       0  4774.8    0.16       0  5015.2    0.07       0
  5020.6    0.16       0
Bank Sta=5015.2,5020.6
Exp/Cntr=0.3,0.1

Type RM Length L Ch R = 1,13009,85,85,85
BEGIN DESCRIPTION:
Elm 52 13009.3
END DESCRIPTION:
XS GIS Cut Line= 3
      1511855.09      6766783.50      1512106.82      6766590.80
      1512257.88      6766378.96
#Sta/Elev= 30
  4679.3 2274.01  4694.0 2273.22  4747.2 2269.89  4776.2 2257.09  4797.1 2254.39
  4805.1 2251.12  4811.6 2246.91  4817.9 2246.06  4826.1 2241.18  4855.1 2231.75
  4861.4 2231.52  4868.1 2228.49  4890.5 2222.10  4905.0 2219.15  4911.3 2219.05
  4954.9 2203.71  4987.5 2200.45  4987.9 2199.95  4992.9 2200.45  5003.8 2200.48
  5018.6 2204.08  5054.2 2205.56  5061.2 2208.56  5069.0 2209.74  5155.0 2211.65
  5169.8 2215.12  5196.8 2227.74  5226.3 2238.50  5233.1 2240.37  5256.5 2240.10
#Mann=4,-1,0
  4679.3    0.07       0  4694.0    0.16       0  4987.5    0.07       0
  4992.9    0.16       0
Bank Sta=4987.5,4992.9
Exp/Cntr=0.3,0.1

Type RM Length L Ch R = 1,12924,126,126,126
BEGIN DESCRIPTION:
Elm 52 12924.13
END DESCRIPTION:
XS GIS Cut Line= 3
      1511952.31      6766849.47      1512186.68      6766615.10
      1512322.09      6766352.96
#Sta/Elev= 30
  4671.3 2263.93  4681.3 2262.52  4716.7 2247.21  4745.0 2238.01  4759.1 2234.71
  4773.2 2232.32  4808.6 2229.43  4851.0 2219.38  4865.2 2218.36  4879.3 2215.02
  4900.5 2212.36  4921.7 2206.38  4950.0 2201.35  4978.3 2201.71  5002.7 2200.25
  5010.5 2198.58  5010.9 2198.08  5015.9 2198.58  5029.7 2200.75  5051.8 2208.22
  5112.0 2209.33  5134.5 2211.25  5162.6 2218.78  5168.3 2223.61  5184.7 2229.17
  5190.8 2232.97  5201.3 2235.74  5213.3 2236.99  5229.0 2236.15  5297.8 2241.39
#Mann=3,-1,0
  4671.3    0.16       0  5010.5    0.07       0  5015.9    0.16       0
Bank Sta=5010.5,5015.9
Exp/Cntr=0.3,0.1

Type RM Length L Ch R = 1,12798,91,91,91
BEGIN DESCRIPTION:
Elm 52 12797.54
END DESCRIPTION:
XS GIS Cut Line= 3
      1512040.86      6766840.79      1512282.16      6766701.91
      1512537.34      6766469.30
#Sta/Elev= 30
  4730.5 2235.50  4770.9 2229.59  4820.2 2225.58  4829.8 2223.72  4845.6 2223.01
  4851.4 2220.73  4941.9 2207.27  4969.2 2201.00  4977.6 2201.00  4985.0 2198.49
  5006.2 2197.08  5006.6 2196.58  5011.6 2197.08  5020.8 2197.19  5041.8 2206.58
  5049.2 2205.85  5098.5 2208.62  5155.3 2209.46  5183.7 2212.46  5226.2 2220.42
  5233.0 2223.16  5240.4 2223.31  5247.2 2226.04  5254.6 2226.15  5268.8 2228.93
  5275.5 2232.16  5283.0 2233.21  5318.1 2244.02  5346.5 2250.80  5354.2 2250.91
#Mann=4,-1,0
  4730.5    0.07       0  4820.2    0.16       0  5006.2    0.07       0
  5011.6    0.16       0
Bank Sta=5006.2,5011.6
Exp/Cntr=0.3,0.1

Type RM Length L Ch R = 1,12707,98,98,98
BEGIN DESCRIPTION:
Elm 52 12706.79
END DESCRIPTION:
XS GIS Cut Line= 3
      1512079.00      6766894.63      1512337.72      6766771.35
      1512605.94      6766522.16
#Sta/Elev= 30
  4712.0 2238.64  4714.5 2235.16  4720.0 2233.35  4737.2 2230.89  4765.4 2230.60
  4788.1 2235.44  4810.8 2233.24  4843.1 2221.46  4884.8 2211.34  4929.8 2207.68
  4952.5 2199.44  5003.5 2195.86  5003.9 2195.36  5009.1 2195.86  5048.8 2203.59
  5197.3 2205.68  5204.2 2208.51  5211.5 2208.57  5218.3 2212.96  5225.7 2212.87
  5232.5 2217.26  5239.8 2217.10  5246.7 2221.16  5254.0 2220.95  5260.8 2225.19
  5275.0 2227.41  5289.2 2232.54  5296.0 2237.77  5317.5 2245.81  5364.7 2254.14
#Mann=4,-1,0
  4712.0    0.07       0  4843.1    0.16       0  5003.5    0.07       0
  5009.1    0.16       0
Bank Sta=5003.5,5009.1
Exp/Cntr=0.3,0.1

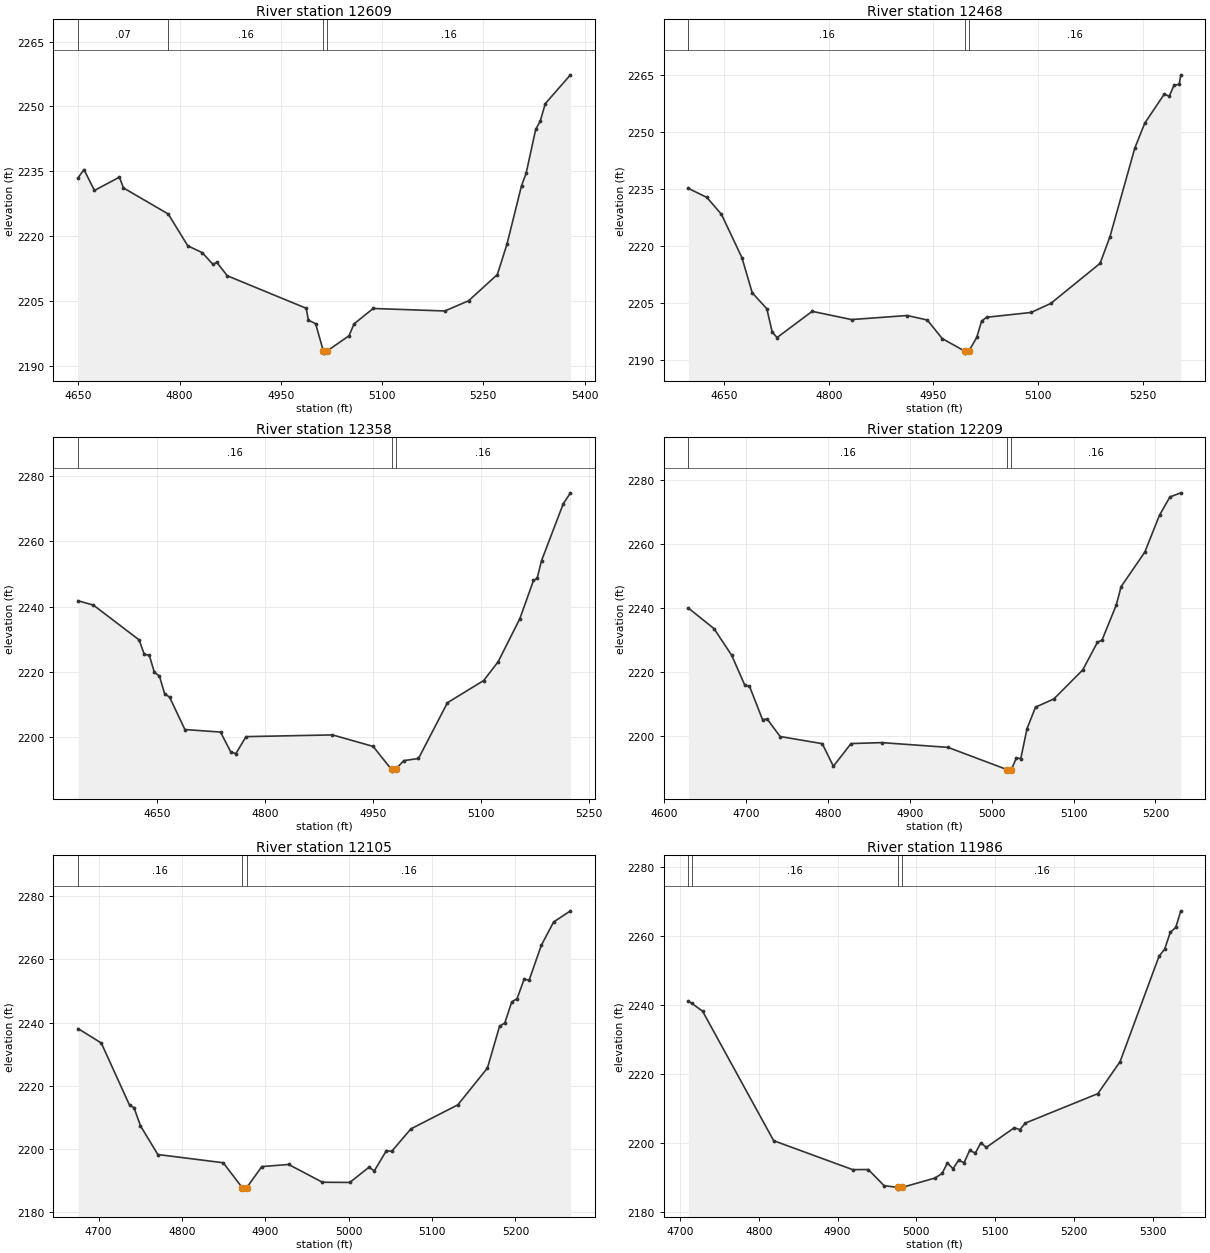
Type RM Length L Ch R = 1,12609,141,141,141
BEGIN DESCRIPTION:
Elm 52 12609.49
END DESCRIPTION:
XS GIS Cut Line= 3
      1512110.30      6767016.14      1512405.43      6766840.80
      1512664.14      6766554.30
#Sta/Elev= 30
  4649.7 2233.45  4658.4 2235.40  4674.0 2230.56  4711.0 2233.63  4716.9 2231.15
  4783.2 2225.12  4812.3 2217.74  4833.7 2216.17  4849.4 2213.47  4855.2 2213.92
  4870.8 2210.82  4987.7 2203.30  4990.8 2200.57  5001.6 2199.73  5013.0 2193.43
  5013.5 2192.93  5018.6 2193.43  5051.0 2196.94  5058.4 2199.68  5086.8 2203.26
  5192.9 2202.68  5228.1 2205.04  5270.7 2211.11  5284.9 2218.10  5306.5 2231.65
  5313.3 2234.50  5327.5 2244.69  5334.2 2246.58  5341.7 2250.64  5379.0 2257.30
#Mann=4,-1,0
  4649.7    0.07       0  4783.2    0.16       0  5013.0    0.07       0
  5018.6    0.16       0
Bank Sta=5013,5018.6
Exp/Cntr=0.3,0.1

Type RM Length L Ch R = 1,12468,110,110,110
BEGIN DESCRIPTION:
Elm 52 12467.94
END DESCRIPTION:
XS GIS Cut Line= 3
      1512315.16      6767165.44      1512546.05      6766846.01
      1512772.25      6766631.90
#Sta/Elev= 30
  4598.8 2235.17  4625.3 2232.79  4646.2 2228.33  4675.6 2216.88  4690.3 2207.64
  4711.2 2203.43  4719.0 2197.27  4725.9 2195.83  4776.2 2202.74  4832.6 2200.57
  4912.3 2201.64  4941.1 2200.46  4962.6 2195.56  4995.0 2192.22  4995.5 2191.72
  5000.6 2192.22  5012.0 2195.85  5019.0 2200.19  5026.2 2201.18  5089.7 2202.44
  5118.0 2204.81  5188.8 2215.40  5202.9 2222.43  5238.5 2245.78  5252.7 2252.34
  5280.7 2260.02  5287.9 2259.48  5294.8 2262.43  5302.1 2262.56  5304.4 2265.11
#Mann=3,-1,0
  4598.8    0.16       0  4995.0    0.07       0  5000.6    0.16       0
Bank Sta=4995,5000.6
Exp/Cntr=0.3,0.1

Type RM Length L Ch R = 1,12358,149,149,149
BEGIN DESCRIPTION:
Elm 52 12358.09
END DESCRIPTION:
XS GIS Cut Line= 3
      1512304.97      6767238.03      1512632.16      6766914.41
      1512855.02      6766938.00
#Sta/Elev= 30
  4539.8 2241.80  4561.1 2240.48  4624.7 2229.80  4631.8 2225.37  4638.8 2225.11
  4645.9 2219.84  4652.9 2218.72  4660.1 2213.33  4667.1 2212.21  4688.3 2202.31
  4737.8 2201.53  4751.9 2195.49  4759.1 2194.90  4773.2 2200.13  4893.4 2200.66
  4949.9 2197.13  4975.4 2190.05  4975.9 2189.55  4981.0 2190.05  4992.4 2192.77
  5012.9 2193.43  5053.1 2210.53  5103.4 2217.33  5123.5 2223.06  5153.7 2236.28
  5172.7 2248.03  5177.7 2248.65  5183.9 2254.11  5214.0 2271.52  5224.1 2274.91
#Mann=3,-1,0
  4539.8    0.16       0  4975.4    0.07       0  4981.0    0.16       0
Bank Sta=4975.4,4981
Exp/Cntr=0.3,0.1

Type RM Length L Ch R = 1,12209,104,104,104
BEGIN DESCRIPTION:
Elm 52 12209.18
END DESCRIPTION:
XS GIS Cut Line= 3
      1512332.55      6767238.34      1512651.95      6767057.81
      1512867.23      6766964.06
#Sta/Elev= 30
  4629.3 2240.07  4660.7 2233.62  4682.3 2225.29  4698.2 2216.01  4704.0 2215.66
  4719.9 2205.24  4725.6 2205.41  4741.5 2199.95  4792.9 2197.73  4806.5 2190.67
  4828.1 2197.76  4865.7 2198.05  4946.5 2196.57  5018.5 2189.65  5019.0 2189.15
  5024.1 2189.65  5030.0 2193.25  5035.5 2193.08  5043.1 2202.39  5053.5 2209.12
  5075.9 2211.69  5111.2 2220.75  5129.2 2229.41  5134.7 2230.03  5152.2 2241.04
  5158.1 2246.76  5187.0 2257.51  5205.0 2269.06  5217.7 2274.73  5231.0 2276.03
#Mann=3,-1,0
  4629.3    0.16       0  5018.5    0.07       0  5024.1    0.16       0
Bank Sta=5018.5,5024.1
Exp/Cntr=0.3,0.1

Type RM Length L Ch R = 1,12105,119,119,119
BEGIN DESCRIPTION:
Elm 52 12104.86
END DESCRIPTION:
XS GIS Cut Line= 3
      1512342.93      6767250.52      1512650.22      6767163.72
      1512868.49      6767002.61
#Sta/Elev= 30
  4675.4 2238.11  4703.3 2233.53  4737.3 2213.79  4742.5 2213.08  4750.3 2207.31
  4771.1 2198.23  4849.6 2195.62  4872.2 2187.77  4872.6 2187.27  4877.8 2187.77
  4895.8 2194.41  4928.0 2195.08  4968.5 2189.45  5001.4 2189.39  5024.4 2194.22
  5030.7 2193.04  5045.3 2199.49  5051.5 2199.20  5074.6 2206.35  5130.9 2213.96
  5166.4 2225.61  5181.0 2238.89  5187.2 2239.86  5195.6 2246.59  5201.9 2247.55
  5210.3 2253.67  5216.5 2253.50  5231.1 2264.52  5245.8 2271.86  5266.0 2275.39
#Mann=3,-1,0
  4675.4    0.16       0  4872.2    0.07       0  4877.8    0.16       0
Bank Sta=4872.2,4877.8
Exp/Cntr=0.3,0.1

Type RM Length L Ch R = 1,11986,239,239,239
BEGIN DESCRIPTION:
Elm 52 11985.94
END DESCRIPTION:
XS GIS Cut Line= 3
      1512316.91      6767281.77      1512634.59      6767262.67
      1512850.77      6767044.77
#Sta/Elev= 30
  4710.6 2241.10  4715.2 2240.44  4728.7 2238.19  4818.9 2200.58  4919.1 2192.18
  4939.1 2192.20  4959.1 2187.52  4976.4 2187.01  4976.8 2186.51  4982.0 2187.01
  5023.8 2189.74  5032.7 2191.06  5039.5 2194.10  5046.6 2192.45  5053.6 2194.84
  5060.7 2194.22  5067.8 2197.78  5074.9 2196.99  5081.9 2199.95  5089.0 2198.65
  5124.4 2204.35  5131.5 2203.79  5138.5 2205.70  5230.5 2214.25  5258.7 2223.53
  5308.2 2254.18  5315.3 2256.21  5322.4 2261.07  5329.5 2262.57  5335.8 2267.35
#Mann=4,-1,0
  4710.6    0.07       0  4715.2    0.16       0  4976.4    0.07       0
  4982.0    0.16       0
Bank Sta=4976.4,4982
Exp/Cntr=0.3,0.1

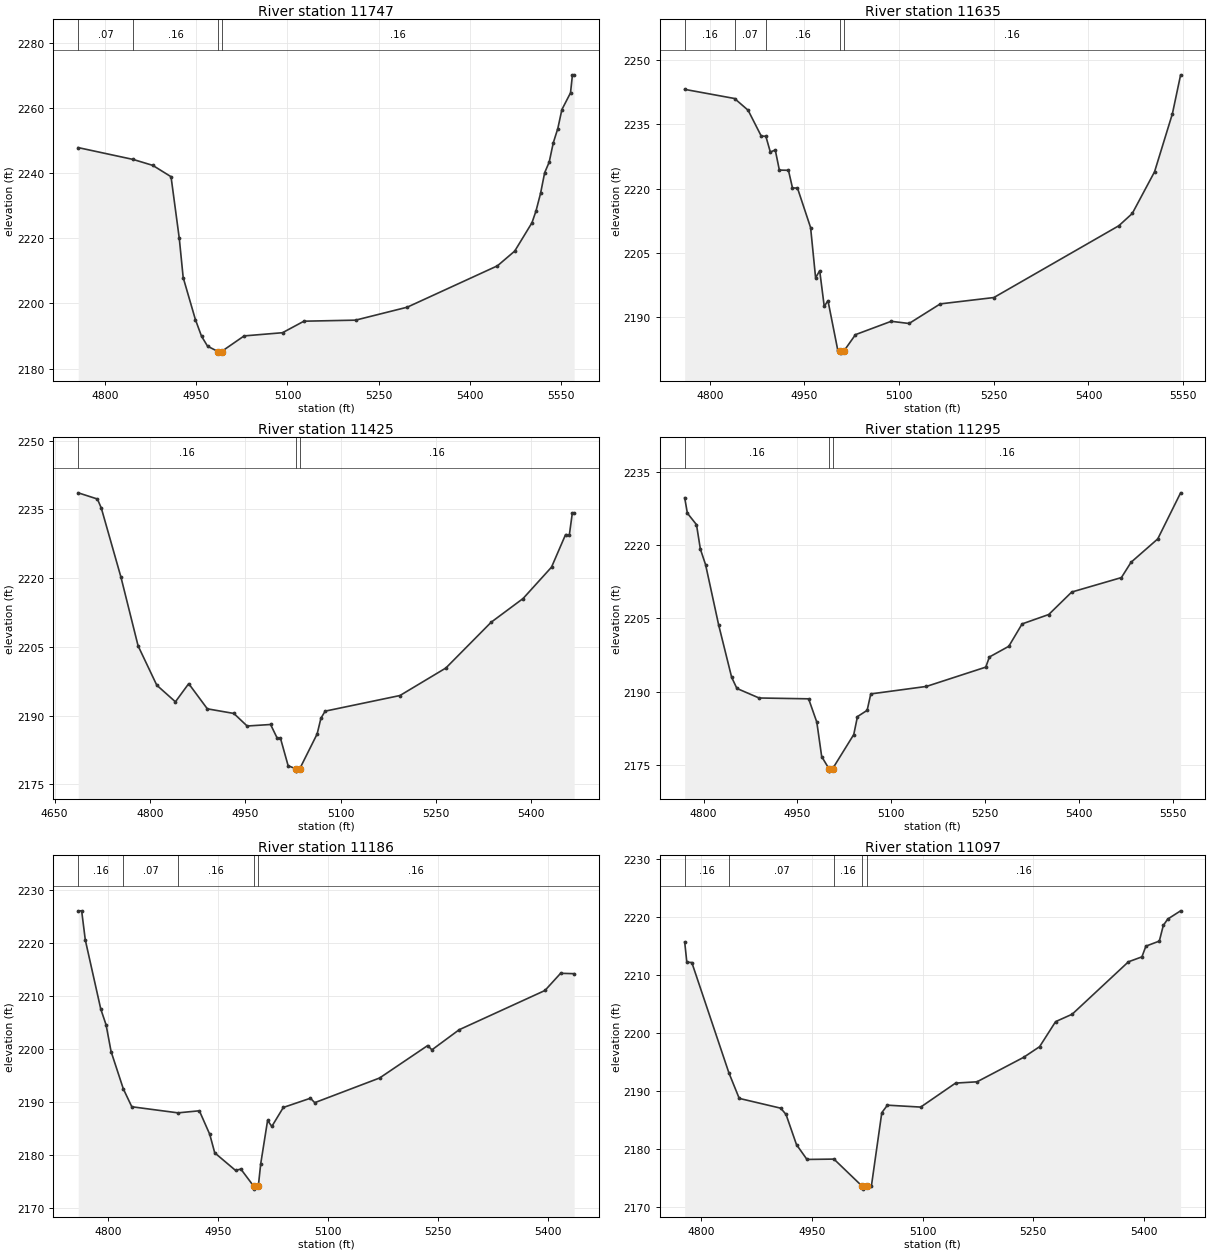
Type RM Length L Ch R = 1,11747,112,112,112
BEGIN DESCRIPTION:
Elm 52 11746.83
END DESCRIPTION:
XS GIS Cut Line= 3
      1512212.72      6767467.53      1512526.95      6767439.76
      1512863.74      6767068.25
#Sta/Elev= 30
  4755.3 2247.87  4846.1 2244.22  4878.1 2242.41  4908.2 2238.93  4921.8 2219.95
  4928.2 2207.95  4948.3 2195.05  4958.4 2189.93  4968.4 2186.85  4985.5 2185.23
  4986.0 2184.73  4991.4 2185.23  5028.6 2190.02  5091.8 2191.00  5127.1 2194.54
  5212.1 2194.86  5297.2 2198.84  5445.9 2211.56  5474.3 2216.08  5502.7 2224.78
  5509.4 2228.43  5516.9 2233.84  5523.6 2240.15  5531.1 2243.42  5537.8 2249.33
  5545.3 2253.74  5552.0 2259.55  5566.2 2264.69  5569.4 2270.23  5572.2 2270.23
#Mann=4,-1,0
  4755.3    0.07       0  4846.1    0.16       0  4985.5    0.07       0
  4991.4    0.16       0
Bank Sta=4985.5,4991.4
Exp/Cntr=0.3,0.1

Type RM Length L Ch R = 1,11635,210,210,210
BEGIN DESCRIPTION:
Elm 52 11635.04
END DESCRIPTION:
XS GIS Cut Line= 3
      1512355.07      6767719.28      1512499.18      6767543.92
      1512890.77      6767145.40
#Sta/Elev= 30
  4760.3 2243.16  4839.3 2241.03  4860.8 2238.29  4881.6 2232.27  4888.9 2232.22
  4896.0 2228.55  4903.8 2229.03  4910.3 2224.34  4924.7 2224.29  4931.1 2220.17
  4939.0 2220.15  4959.8 2210.93  4967.7 2199.23  4974.2 2200.88  4981.4 2192.55
  4987.3 2193.90  5002.7 2182.46  5006.7 2182.16  5007.2 2181.66  5012.6 2182.16
  5030.9 2185.97  5087.5 2189.08  5115.8 2188.57  5165.2 2193.14  5250.1 2194.62
  5448.1 2211.36  5469.4 2214.22  5504.7 2223.94  5533.0 2237.49  5546.0 2246.55
#Mann=5,-1,0
  4760.3    0.16       0  4839.3    0.07       0  4888.9    0.16       0
  5006.7    0.07       0  5012.6    0.16       0
Bank Sta=5006.7,5012.6
Exp/Cntr=0.3,0.1

Type RM Length L Ch R = 1,11425,130,130,130
BEGIN DESCRIPTION:
Elm 52 11425.156
END DESCRIPTION:
XS GIS Cut Line= 3
      1512450.58      6767766.14      1512703.22      6767581.70
      1512954.98      6767188.02
#Sta/Elev= 30
  4687.2 2238.61  4717.4 2237.26  4723.6 2235.25  4754.4 2220.23  4781.4 2205.23
  4810.8 2196.65  4840.1 2193.03  4861.0 2196.99  4890.3 2191.50  4932.0 2190.49
  4952.9 2187.75  4989.8 2188.08  5000.0 2185.16  5005.2 2185.16  5017.4 2179.09
  5029.7 2178.41  5030.2 2177.91  5035.6 2178.41  5063.0 2186.01  5069.0 2189.45
  5075.6 2190.99  5193.3 2194.40  5265.5 2200.40  5336.8 2210.39  5387.0 2215.56
  5431.7 2222.40  5453.8 2229.50  5459.7 2229.40  5464.4 2234.17  5467.3 2234.17
#Mann=3,-1,0
  4687.2    0.16       0  5029.7    0.07       0  5035.6    0.16       0
Bank Sta=5029.7,5035.6
Exp/Cntr=0.3,0.1

Type RM Length L Ch R = 1,11295,109,109,109
BEGIN DESCRIPTION:
Elm 52 11294.72
END DESCRIPTION:
XS GIS Cut Line= 3
      1512575.55      6767814.77      1512752.65      6767682.81
      1513050.62      6767194.27
#Sta/Elev= 30
  4769.8 2229.66  4774.1 2226.50  4788.7 2224.15  4794.9 2219.16  4803.3 2215.95
  4824.1 2203.70  4844.9 2193.00  4853.3 2190.72  4888.8 2188.77  4968.0 2188.60
  4981.1 2183.84  4988.9 2176.81  5000.5 2174.34  5001.0 2173.84  5006.4 2174.34
  5040.2 2181.31  5046.1 2184.97  5061.6 2186.25  5067.4 2189.60  5156.4 2191.13
  5251.3 2195.07  5257.1 2197.14  5288.1 2199.32  5309.4 2203.89  5352.0 2205.81
  5388.8 2210.40  5468.2 2213.35  5483.6 2216.47  5526.3 2221.24  5562.9 2230.65
#Mann=3,-1,0
  4769.8    0.16       0  5000.5    0.07       0  5006.4    0.16       0
Bank Sta=5000.5,5006.4
Exp/Cntr=0.3,0.1

Type RM Length L Ch R = 1,11186,89,89,89
BEGIN DESCRIPTION:
Elm 52 11185.87
END DESCRIPTION:
XS GIS Cut Line= 3
      1512683.18      6767859.92      1512860.29      6767693.23
      1513080.41      6767318.85
#Sta/Elev= 30
  4758.9 2226.05  4763.6 2226.05  4768.6 2220.54  4789.7 2207.54  4797.0 2204.54
  4803.8 2199.52  4820.5 2192.49  4832.1 2189.11  4895.2 2187.96  4924.4 2188.35
  4938.6 2183.91  4945.4 2180.42  4973.8 2177.11  4981.1 2177.36  4998.9 2174.08
  4999.4 2173.58  5004.9 2174.08  5008.2 2178.34  5017.6 2186.53  5023.4 2185.40
  5039.1 2188.98  5076.2 2190.72  5082.0 2189.88  5170.6 2194.53  5236.3 2200.65
  5242.1 2199.84  5279.3 2203.63  5396.5 2211.03  5417.9 2214.27  5436.4 2214.20
#Mann=5,-1,0
  4758.9    0.16       0  4820.5    0.07       0  4895.2    0.16       0
  4998.9    0.07       0  5004.9    0.16       0
Bank Sta=4998.9,5004.9
Exp/Cntr=0.3,0.1

Type RM Length L Ch R = 1,11097,123,123,123
BEGIN DESCRIPTION:
Elm 52 11096.59
END DESCRIPTION:
XS GIS Cut Line= 3
      1512757.87      6767905.02      1512922.79      6767757.47
      1513099.39      6767341.93
#Sta/Elev= 30
  4777.3 2215.70  4780.2 2212.20  4787.0 2212.13  4837.3 2193.10  4851.3 2188.70
  4907.6 2187.01  4914.8 2185.93  4929.0 2180.72  4943.2 2178.17  4979.8 2178.23
  5018.1 2173.55  5018.6 2173.05  5024.1 2173.55  5030.6 2173.57  5044.7 2186.23
  5052.3 2187.53  5097.5 2187.20  5144.8 2191.34  5173.9 2191.56  5237.1 2195.78
  5258.8 2197.62  5280.5 2201.94  5303.0 2203.22  5379.3 2212.26  5397.6 2213.11
  5403.0 2214.96  5421.2 2215.83  5426.6 2218.53  5432.6 2219.63  5450.1 2221.05
#Mann=5,-1,0
  4777.3    0.16       0  4837.3    0.07       0  4979.8    0.16       0
  5018.1    0.07       0  5024.1    0.16       0
Bank Sta=5018.1,5024.1
Exp/Cntr=0.3,0.1