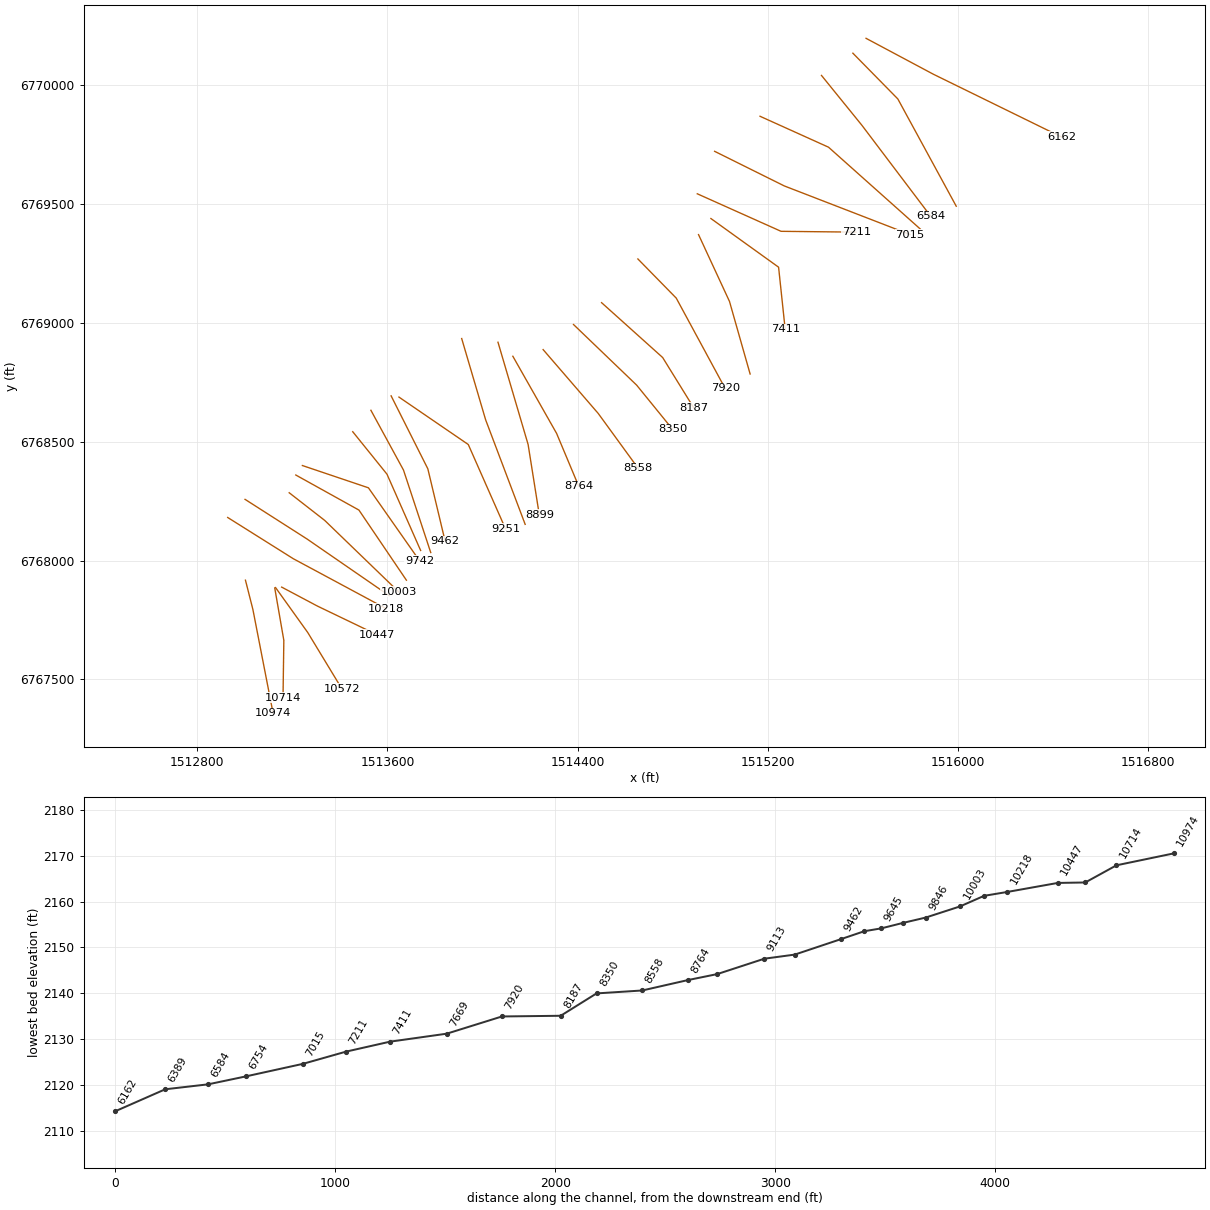
HEC-RAS study Elm 52.prj: Elm 52 Base Level Engineering

--- Elm 52.g01 (geometry) --- (continued)

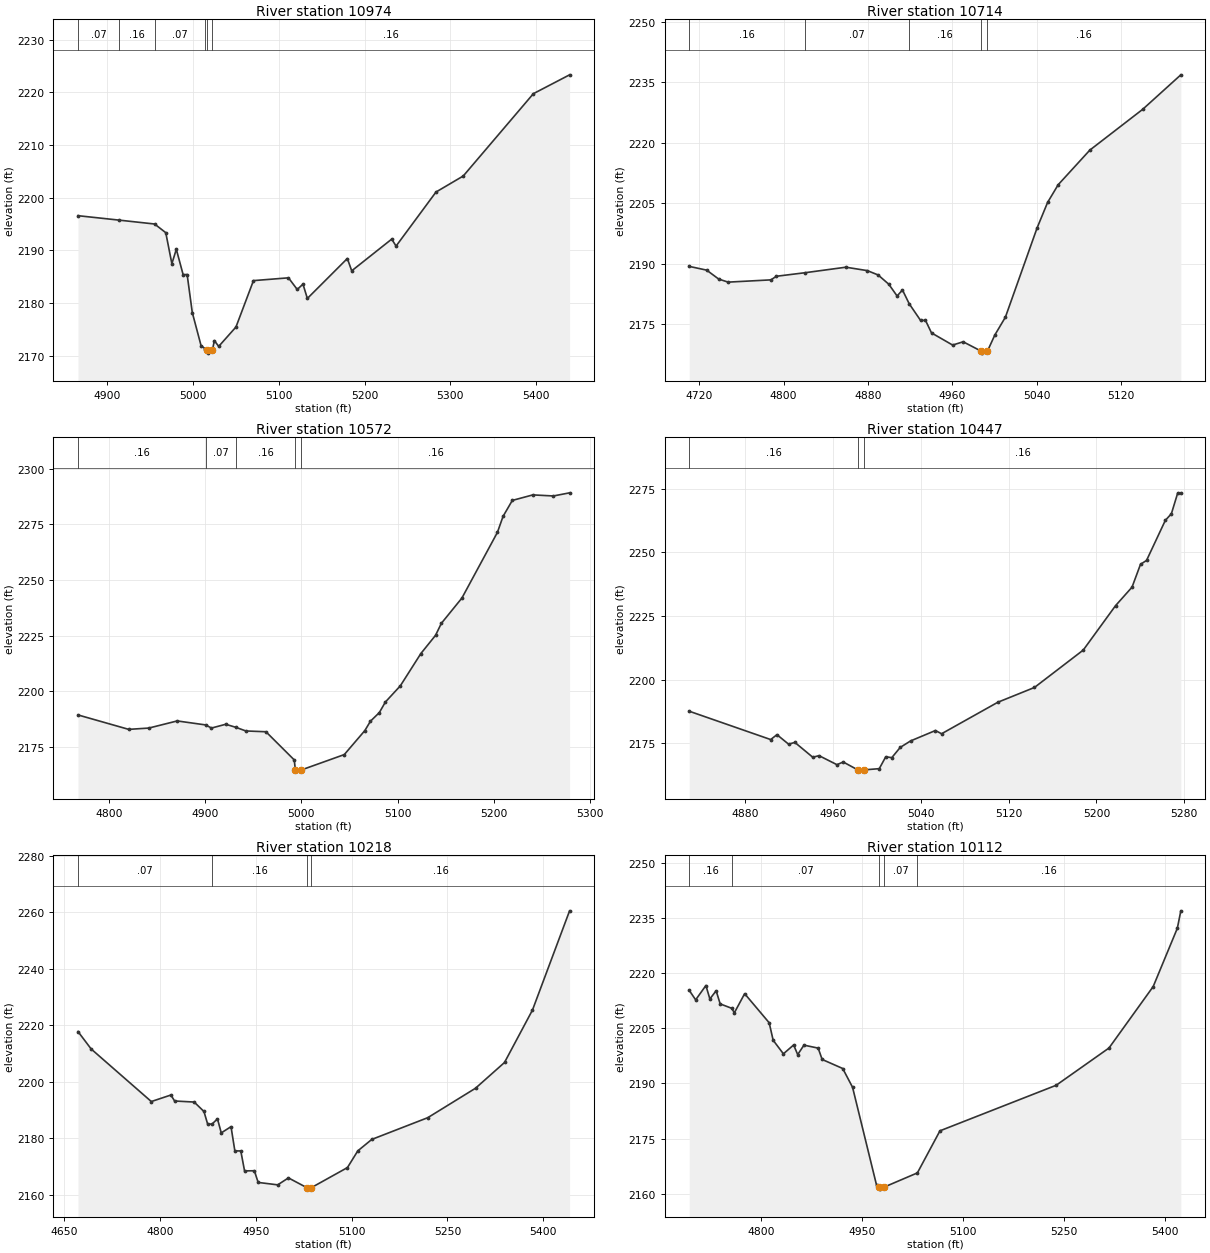
Type RM Length L Ch R = 1,10974,260,260,260
BEGIN DESCRIPTION:
Elm 52 10973.66
END DESCRIPTION:
XS GIS Cut Line= 3
      1513002.65      6767917.19      1513033.90      6767793.92
      1513118.97      6767356.39
#Sta/Elev= 30
  4866.0 2196.58  4913.8 2195.74  4955.3 2195.00  4968.3 2193.35  4975.4 2187.47
  4980.6 2190.20  4988.5 2185.40  4993.2 2185.40  4999.2 2178.19  5009.4 2171.92
  5014.0 2171.32  5016.6 2170.98  5017.1 2170.48  5022.6 2170.98  5024.9 2172.86
  5030.0 2171.76  5050.1 2175.44  5070.5 2184.25  5111.3 2184.78  5121.5 2182.57
  5128.2 2183.58  5133.3 2180.86  5179.9 2188.45  5185.0 2186.11  5231.6 2192.13
  5236.7 2190.81  5283.2 2201.07  5315.0 2204.12  5396.7 2219.75  5438.9 2223.33
#Mann=6,-1,0
  4866.0    0.07       0  4913.8    0.16       0  4955.3    0.07       0
  5014.0    0.16       0  5016.6    0.07       0  5022.6    0.16       0
Bank Sta=5016.6,5022.6
Exp/Cntr=0.3,0.1

Type RM Length L Ch R = 1,10714,142,142,142
BEGIN DESCRIPTION:
Elm 52 10714.11
END DESCRIPTION:
XS GIS Cut Line= 3
      1513125.90      6767884.25      1513164.11      6767663.72
      1513160.65      6767421.86
#Sta/Elev= 30
  4710.7 2189.38  4727.2 2188.45  4738.6 2186.24  4747.5 2185.48  4788.1 2186.04
  4793.2 2186.93  4820.1 2187.80  4859.1 2189.18  4879.4 2188.33  4889.6 2187.26
  4899.7 2184.97  4907.6 2182.05  4912.7 2183.53  4919.1 2180.11  4929.8 2176.01
  4934.5 2176.01  4940.2 2172.90  4960.2 2169.89  4970.2 2170.70  4987.2 2168.39
  4987.7 2167.89  4993.2 2168.39  5000.2 2172.38  5010.2 2176.80  5040.2 2198.89
  5050.2 2205.24  5060.2 2209.61  5090.2 2218.19  5140.3 2228.30  5176.4 2236.84
#Mann=5,-1,0
  4710.7    0.16       0  4820.1    0.07       0  4919.1    0.16       0
  4987.2    0.07       0  4993.2    0.16       0
Bank Sta=4987.2,4993.2
Exp/Cntr=0.3,0.1

Type RM Length L Ch R = 1,10572,125,125,125
BEGIN DESCRIPTION:
Elm 52 10572.35
END DESCRIPTION:
XS GIS Cut Line= 3
      1513129.37      6767885.96      1513264.80      6767696.70
      1513408.89      6767458.87
#Sta/Elev= 30
  4768.0 2189.38  4820.7 2182.90  4841.6 2183.49  4871.1 2186.69  4900.6 2184.90
  4906.7 2183.49  4921.5 2185.19  4931.9 2183.84  4942.4 2182.19  4963.3 2181.83
  4992.7 2169.18  4993.9 2164.65  4994.4 2164.15  4999.9 2164.65  5044.7 2171.58
  5066.1 2182.38  5071.9 2186.58  5081.1 2190.42  5087.4 2195.18  5102.9 2202.43
  5124.3 2216.97  5139.5 2225.12  5145.6 2230.53  5166.9 2241.86  5203.8 2271.35
  5209.7 2278.57  5219.3 2285.71  5240.6 2288.19  5262.0 2287.71  5278.8 2289.12
#Mann=5,-1,0
  4768.0    0.16       0  4900.6    0.07       0  4931.9    0.16       0
  4993.9    0.07       0  4999.9    0.16       0
Bank Sta=4993.9,4999.9
Exp/Cntr=0.3,0.1

Type RM Length L Ch R = 1,10447,229,229,229
BEGIN DESCRIPTION:
Elm 52 10446.998
END DESCRIPTION:
XS GIS Cut Line= 3
      1513155.02      6767887.99      1513305.61      6767808.05
      1513555.02      6767687.99
#Sta/Elev= 30
  4829.5 2187.58  4903.6 2176.45  4909.3 2178.37  4919.9 2174.64  4925.6 2175.34
  4941.9 2169.50  4947.6 2170.13  4963.9 2166.58  4969.6 2167.64  4982.8 2164.55
  4983.3 2164.05  4988.9 2164.55  5002.4 2165.02  5008.3 2169.69  5013.8 2169.34
  5021.5 2173.38  5030.9 2175.91  5053.5 2180.00  5059.1 2178.73  5110.3 2191.11
  5143.6 2196.91  5188.0 2211.60  5217.4 2229.05  5232.4 2236.32  5240.1 2245.29
  5245.6 2246.82  5262.7 2262.56  5268.2 2265.15  5274.0 2273.37  5276.8 2273.37
#Mann=3,-1,0
  4829.5    0.16       0  4982.8    0.07       0  4988.9    0.16       0
Bank Sta=4982.8,4988.9
Exp/Cntr=0.3,0.1

Type RM Length L Ch R = 1,10218,106,106,106
BEGIN DESCRIPTION:
Elm 52 10217.97
END DESCRIPTION:
XS GIS Cut Line= 3
      1512927.96      6768181.10      1513204.04      6768007.47
      1513594.69      6767797.38
#Sta/Elev= 30
  4671.5 2217.79  4692.1 2211.63  4786.3 2193.05  4816.9 2195.35  4822.8 2193.24
  4853.4 2192.87  4868.7 2189.54  4874.6 2185.01  4881.6 2185.14  4889.9 2186.93
  4895.8 2181.97  4911.1 2184.17  4917.1 2175.61  4926.4 2175.59  4932.3 2168.54
  4947.6 2168.58  4953.6 2164.46  4984.2 2163.60  5001.0 2166.06  5030.0 2162.59
  5030.5 2162.09  5036.7 2162.59  5093.4 2169.71  5109.6 2175.61  5131.5 2179.66
  5219.2 2187.35  5293.9 2197.75  5339.3 2206.85  5383.1 2225.39  5441.2 2260.46
#Mann=4,-1,0
  4671.5    0.07       0  4881.6    0.16       0  5030.0    0.07       0
  5036.7    0.16       0
Bank Sta=5030,5036.7
Exp/Cntr=0.3,0.1

Type RM Length L Ch R = 1,10112,109,109,109
BEGIN DESCRIPTION:
Elm 52 10111.76
END DESCRIPTION:
XS GIS Cut Line= 3
      1513000.94      6768257.45      1513261.33      6768090.80
      1513607.23      6767852.13
#Sta/Elev= 30
  4693.5 2215.27  4703.0 2212.69  4718.2 2216.59  4724.1 2212.94  4733.4 2215.16
  4739.4 2211.59  4756.2 2210.42  4760.5 2209.20  4775.7 2214.37  4812.1 2206.46
  4818.0 2201.71  4833.2 2198.02  4848.4 2200.43  4854.4 2197.81  4863.7 2200.38
  4884.8 2199.57  4890.7 2196.49  4921.2 2194.03  4935.8 2188.93  4971.4 2162.33
  4975.3 2161.74  4975.8 2161.24  4982.0 2161.74  5032.0 2165.65  5065.5 2177.09
  5237.9 2189.47  5316.3 2199.60  5381.9 2216.31  5417.7 2232.15  5422.9 2236.89
#Mann=5,-1,0
  4693.5    0.16       0  4756.2    0.07       0  4975.3    0.07       0
  4982.0    0.07       0  5032.0    0.16       0
Bank Sta=4975.3,4982
Exp/Cntr=0.3,0.1

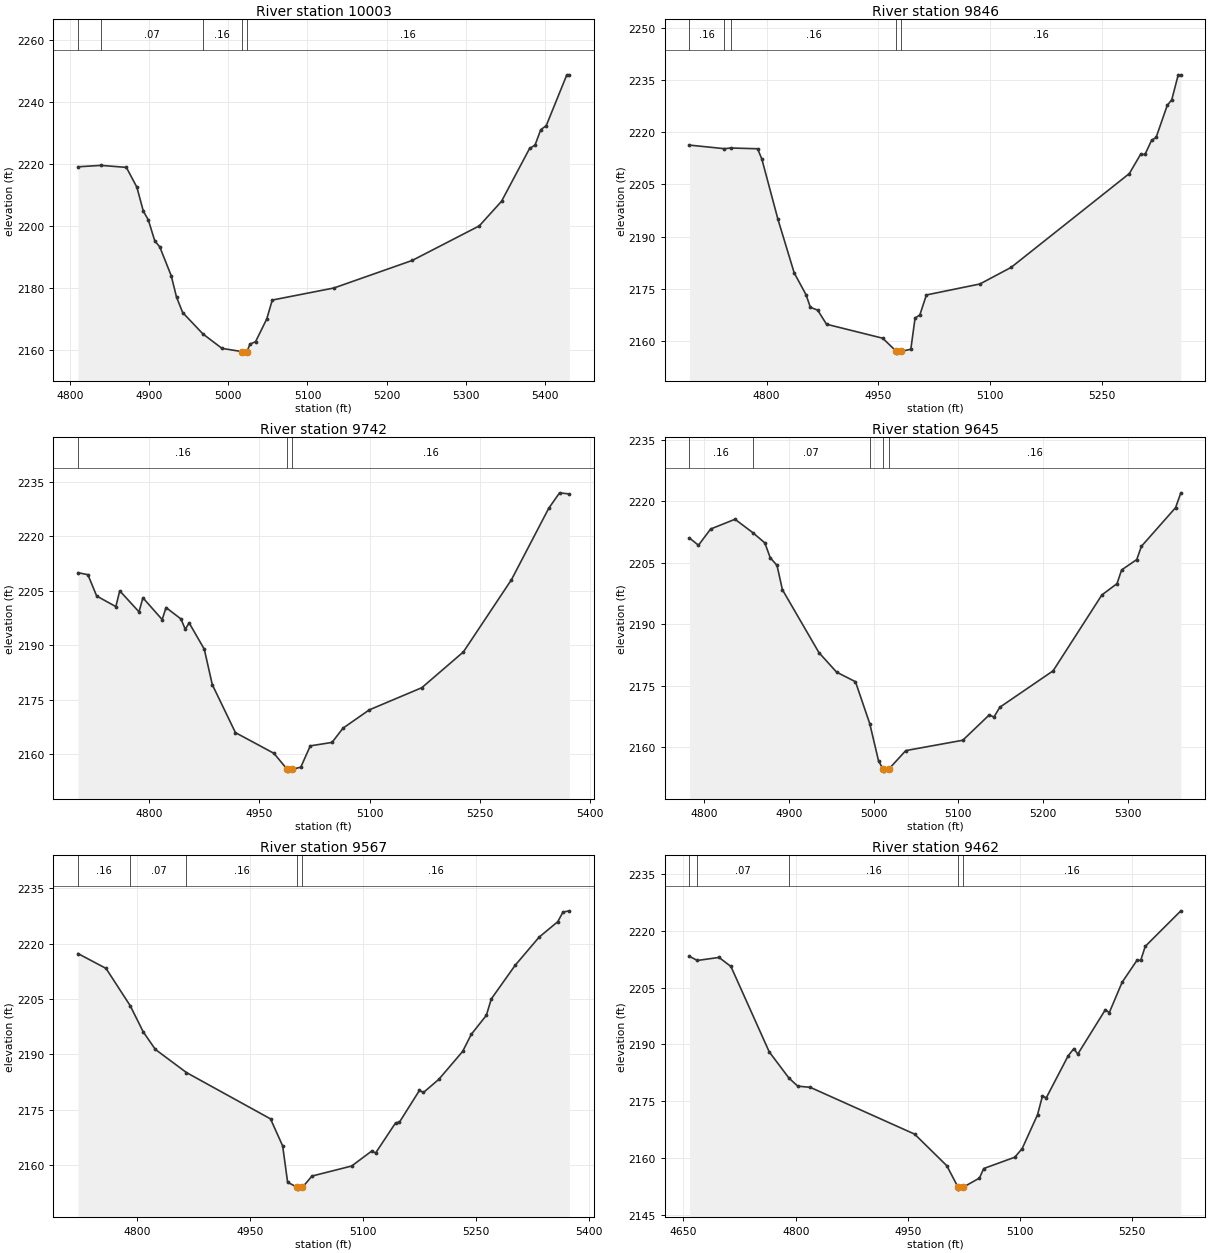
Type RM Length L Ch R = 1,10003,157,157,157
BEGIN DESCRIPTION:
Elm 52 10003.14
END DESCRIPTION:
XS GIS Cut Line= 3
      1513186.72      6768285.21      1513335.98      6768168.92
      1513646.74      6767868.58
#Sta/Elev= 30
  4809.8 2219.05  4838.9 2219.51  4871.0 2218.86  4884.3 2212.45  4892.4 2204.77
  4898.7 2201.94  4906.9 2195.16  4913.2 2193.23  4927.7 2183.92  4934.4 2177.03
  4942.2 2172.03  4967.9 2165.11  4991.9 2160.47  5016.9 2159.44  5017.4 2158.94
  5023.6 2159.44  5027.2 2161.82  5034.4 2162.64  5048.5 2169.95  5055.5 2176.06
  5133.4 2179.95  5232.4 2188.83  5317.3 2199.99  5345.4 2207.91  5380.9 2224.96
  5387.8 2226.04  5395.0 2231.00  5402.0 2232.34  5428.0 2248.72  5431.2 2248.72
#Mann=5,-1,0
  4809.8    0.16       0  4838.9    0.07       0  4967.9    0.16       0
  5016.9    0.07       0  5023.6    0.16       0
Bank Sta=5016.9,5023.6
Exp/Cntr=0.3,0.1

Type RM Length L Ch R = 1,9846,104,104,104
BEGIN DESCRIPTION:
Elm 52 9846.01
END DESCRIPTION:
XS GIS Cut Line= 3
      1513214.47      6768359.89      1513480.08      6768212.33
      1513679.75      6767917.16
#Sta/Elev= 30
  4696.3 2216.32  4743.3 2215.29  4751.9 2215.49  4787.8 2215.27  4793.5 2212.33
  4815.2 2194.95  4837.0 2179.58  4853.0 2173.26  4858.7 2169.67  4868.5 2168.88
  4880.4 2164.81  4955.9 2160.79  4974.3 2157.00  4974.8 2156.50  4981.0 2157.00
  4993.7 2157.63  4999.4 2166.58  5005.8 2167.47  5014.6 2173.23  5086.5 2176.38
  5128.5 2181.16  5287.3 2208.14  5302.3 2213.63  5308.3 2213.62  5317.2 2217.71
  5323.3 2218.55  5338.2 2227.74  5344.3 2229.38  5353.0 2236.53  5356.5 2236.53
#Mann=5,-1,0
  4696.3    0.16       0  4743.3    0.07       0  4751.9    0.16       0
  4974.3    0.07       0  4981.0    0.16       0
Bank Sta=4974.3,4981
Exp/Cntr=0.3,0.1

Type RM Length L Ch R = 1,9742,97,97,97
BEGIN DESCRIPTION:
Elm 52 9742.44
END DESCRIPTION:
XS GIS Cut Line= 3
      1513242.21      6768399.83      1513520.01      6768306.08
      1513735.29      6767998.78
#Sta/Elev= 30
  4703.2 2209.92  4716.7 2209.37  4728.6 2203.51  4754.7 2200.59  4760.0 2204.93
  4786.2 2199.15  4791.5 2203.02  4817.7 2197.03  4823.0 2200.33  4843.3 2197.19
  4849.1 2194.36  4854.4 2196.11  4875.0 2188.88  4885.9 2179.12  4917.4 2165.92
  4969.7 2160.24  4987.8 2155.83  4988.3 2155.33  4994.5 2155.83  5006.3 2156.42
  5019.2 2162.28  5048.8 2163.23  5063.6 2167.13  5099.4 2172.18  5170.9 2178.28
  5227.5 2188.13  5292.9 2208.01  5343.5 2227.62  5358.3 2231.89  5371.6 2231.58
#Mann=3,-1,0
  4703.2    0.16       0  4987.8    0.07       0  4994.5    0.16       0
Bank Sta=4987.8,4994.5
Exp/Cntr=0.3,0.1

Type RM Length L Ch R = 1,9645,78,78,78
BEGIN DESCRIPTION:
Elm 52 9644.76
END DESCRIPTION:
XS GIS Cut Line= 3
      1513454.06      6768542.16      1513598.13      6768363.37
      1513739.68      6768042.30
#Sta/Elev= 30
  4782.5 2211.05  4793.1 2209.29  4807.5 2213.25  4836.3 2215.63  4857.3 2212.36
  4871.5 2209.87  4877.9 2206.24  4885.9 2204.37  4892.3 2198.43  4935.5 2183.07
  4956.3 2178.32  4978.6 2175.98  4995.5 2165.73  5005.9 2156.62  5011.3 2154.66
  5011.8 2154.16  5018.0 2154.66  5038.0 2159.17  5105.4 2161.70  5136.7 2167.89
  5142.2 2167.35  5149.1 2169.75  5212.1 2178.64  5269.7 2197.16  5287.6 2199.92
  5293.0 2203.26  5310.9 2205.79  5316.4 2209.02  5356.8 2218.47  5363.0 2222.08
#Mann=5,-1,0
  4782.5    0.16       0  4857.3    0.07       0  4995.5    0.16       0
  5011.3    0.07       0  5018.0    0.16       0
Bank Sta=5011.3,5018
Exp/Cntr=0.3,0.1

Type RM Length L Ch R = 1,9567,105,105,105
BEGIN DESCRIPTION:
Elm 52 9567.36
END DESCRIPTION:
XS GIS Cut Line= 3
      1513530.45      6768632.42      1513667.58      6768380.73
      1513782.17      6768033.47
#Sta/Elev= 30
  4721.6 2217.34  4758.8 2213.33  4790.9 2203.23  4808.2 2196.14  4824.3 2191.38
  4865.6 2185.11  4977.2 2172.56  4993.3 2165.24  4999.9 2155.38  5012.8 2154.03
  5013.3 2153.53  5019.6 2154.03  5032.2 2157.07  5084.9 2159.79  5111.4 2163.82
  5116.7 2163.32  5143.2 2171.47  5148.4 2171.69  5174.9 2180.28  5180.2 2179.71
  5200.6 2183.27  5232.2 2190.82  5243.7 2195.46  5263.8 2200.64  5270.2 2205.03
  5301.9 2214.15  5333.7 2221.78  5358.6 2225.99  5365.4 2228.58  5373.9 2228.92
#Mann=5,-1,0
  4721.6    0.16       0  4790.9    0.07       0  4865.6    0.16       0
  5012.8    0.07       0  5019.6    0.16       0
Bank Sta=5012.8,5019.6
Exp/Cntr=0.3,0.1

Type RM Length L Ch R = 1,9462,211,211,211
BEGIN DESCRIPTION:
Elm 52 9461.88
END DESCRIPTION:
XS GIS Cut Line= 3
      1513615.49      6768693.25      1513770.01      6768385.94
      1513842.62      6768081.65
#Sta/Elev= 30
  4658.0 2213.26  4668.5 2212.17  4697.5 2212.97  4713.4 2210.58  4764.6 2188.05
  4790.8 2181.17  4802.7 2179.00  4819.4 2178.69  4959.0 2166.33  5002.0 2157.99
  5017.0 2152.32  5017.5 2151.82  5023.8 2152.32  5045.6 2154.74  5051.3 2157.26
  5092.8 2160.24  5102.7 2162.53  5123.2 2171.44  5129.8 2176.38  5134.9 2175.92
  5164.3 2187.05  5171.9 2188.92  5177.0 2187.45  5214.0 2199.20  5219.1 2198.39
  5236.3 2206.42  5256.1 2212.19  5261.2 2212.22  5267.2 2215.89  5314.8 2225.27
#Mann=5,-1,0
  4658.0    0.16       0  4668.5    0.07       0  4790.8    0.16       0
  5017.0    0.07       0  5023.8    0.16       0
Bank Sta=5017,5023.8
Exp/Cntr=0.3,0.1

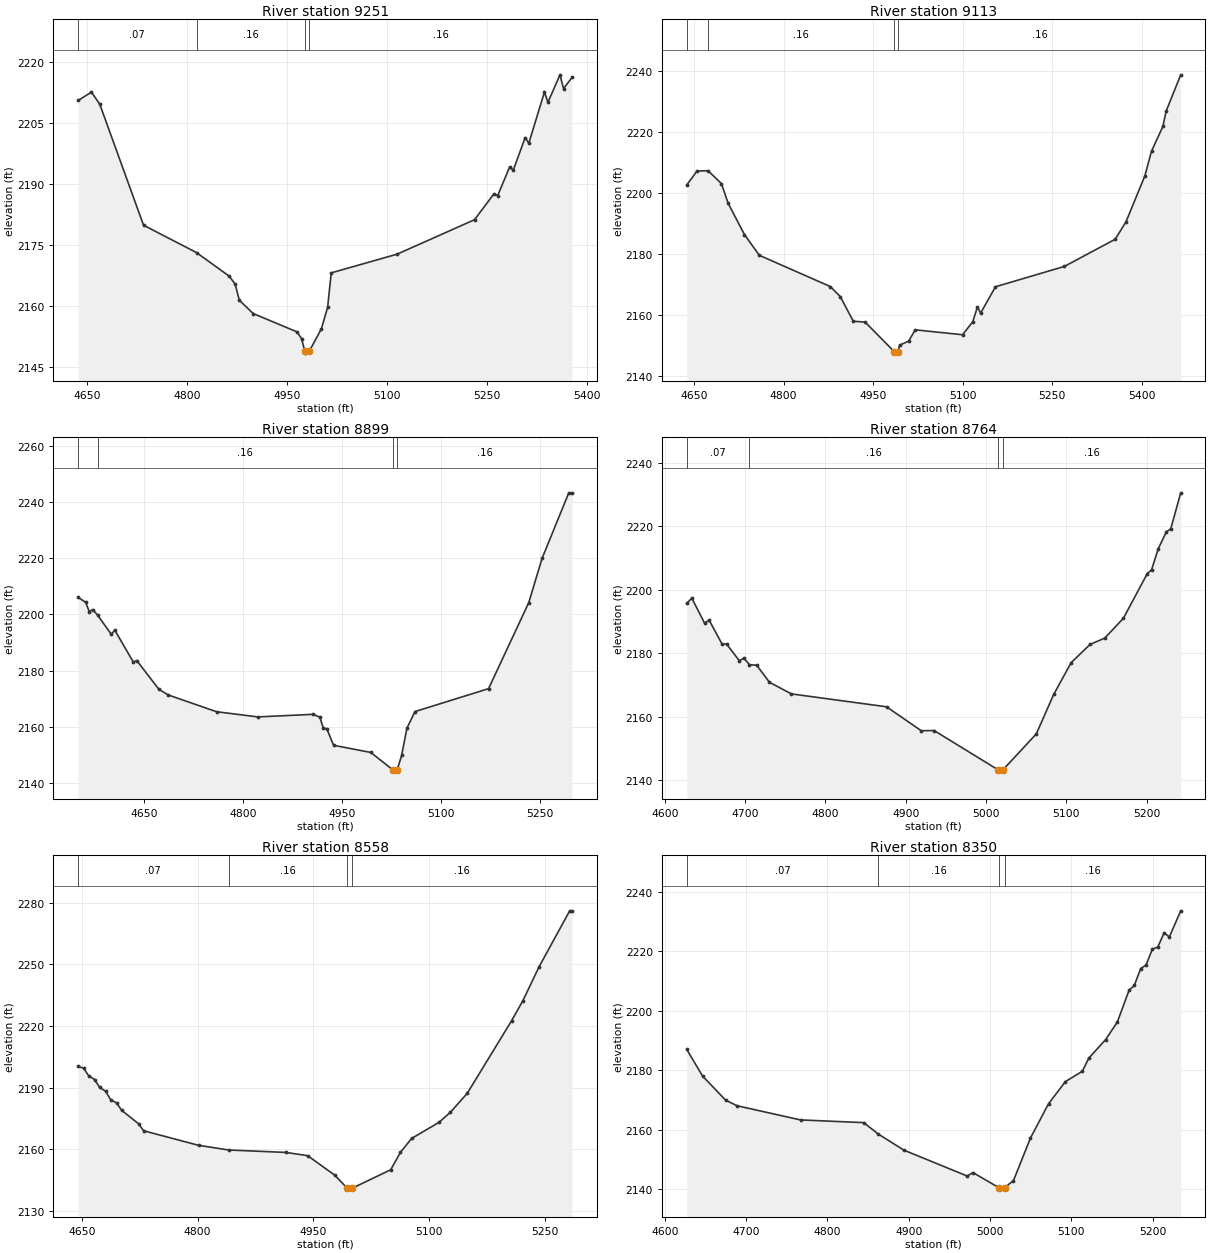
Type RM Length L Ch R = 1,9251,138,138,138
BEGIN DESCRIPTION:
Elm 52 9250.66
END DESCRIPTION:
XS GIS Cut Line= 3
      1513648.47      6768688.03      1513940.15      6768488.37
      1514096.41      6768134.18
#Sta/Elev= 30
  4636.5 2210.49  4656.5 2212.53  4668.9 2209.59  4734.6 2179.85  4814.0 2173.13
  4863.2 2167.32  4872.1 2165.34  4878.1 2161.44  4899.1 2158.15  4964.8 2153.65
  4971.6 2151.95  4976.3 2148.94  4976.8 2148.44  4983.2 2148.94  5001.3 2154.44
  5010.6 2159.71  5016.0 2168.15  5114.8 2172.74  5230.8 2181.20  5260.1 2187.59
  5265.6 2187.13  5283.5 2194.15  5288.9 2193.37  5306.8 2201.37  5312.2 2199.97
  5335.6 2212.51  5341.0 2210.05  5358.9 2216.78  5364.3 2213.40  5377.1 2216.14
#Mann=4,-1,0
  4636.5    0.07       0  4814.0    0.16       0  4976.3    0.07       0
  4983.2    0.16       0
Bank Sta=4976.3,4983.2
Exp/Cntr=0.3,0.1

Type RM Length L Ch R = 1,9113,214,214,214
BEGIN DESCRIPTION:
Elm 52 9113.26
END DESCRIPTION:
XS GIS Cut Line= 3
      1513912.38      6768934.53      1514013.07      6768592.53
      1514179.48      6768152.24
#Sta/Elev= 30
  4637.9 2202.58  4655.1 2207.14  4673.7 2207.25  4696.0 2203.02  4707.3 2196.55
  4734.5 2186.36  4759.4 2179.57  4878.3 2169.34  4894.9 2166.08  4916.8 2157.98
  4936.6 2157.71  4985.3 2148.05  4985.8 2147.55  4992.2 2148.05  4994.2 2150.16
  5009.3 2151.45  5020.6 2155.17  5099.8 2153.57  5116.9 2157.85  5124.7 2162.67
  5130.0 2160.65  5154.9 2169.27  5270.2 2175.92  5355.4 2184.82  5373.4 2190.50
  5405.1 2205.56  5416.2 2213.66  5435.3 2221.76  5440.6 2226.70  5465.1 2238.63
#Mann=4,-1,0
  4637.9    0.07       0  4673.7    0.16       0  4985.3    0.07       0
  4992.2    0.16       0
Bank Sta=4985.3,4992.2
Exp/Cntr=0.3,0.1

Type RM Length L Ch R = 1,8899,135,135,135
BEGIN DESCRIPTION:
Elm 52 8899.19
END DESCRIPTION:
XS GIS Cut Line= 3
      1514065.14      6768918.94      1514191.88      6768488.37
      1514238.76      6768193.20
#Sta/Elev= 30
  4550.7 2206.08  4562.1 2204.35  4567.6 2201.00  4572.8 2201.75  4580.1 2199.80
  4600.9 2192.94  4606.2 2194.42  4634.3 2183.03  4639.5 2183.58  4672.8 2173.39
  4687.2 2171.33  4760.2 2165.36  4822.7 2163.51  4906.1 2164.43  4916.5 2163.45
  4921.9 2159.48  4927.1 2159.30  4937.4 2153.41  4993.8 2150.85  5026.8 2144.70
  5027.3 2144.20  5033.7 2144.70  5040.4 2149.78  5048.4 2159.50  5060.7 2165.42
  5172.0 2173.58  5232.8 2204.21  5253.0 2219.98  5293.4 2243.33  5298.4 2243.33
#Mann=4,-1,0
  4550.7    0.07       0  4580.1    0.16       0  5026.8    0.07       0
  5033.7    0.16       0
Bank Sta=5026.8,5033.7
Exp/Cntr=0.3,0.1

Type RM Length L Ch R = 1,8764,206,206,206
BEGIN DESCRIPTION:
Elm 52 8764.05
END DESCRIPTION:
XS GIS Cut Line= 3
      1514127.65      6768859.89      1514311.68      6768535.24
      1514405.05      6768312.17
#Sta/Elev= 30
  4627.3 2195.66  4633.6 2197.31  4649.5 2189.45  4655.3 2190.33  4671.2 2182.90
  4676.9 2182.88  4692.8 2177.60  4698.5 2178.43  4705.4 2176.37  4714.4 2176.21
  4730.3 2170.83  4757.7 2167.18  4876.0 2163.13  4919.3 2155.59  4935.2 2155.66
  5014.4 2143.38  5014.9 2142.88  5021.3 2143.38  5062.5 2154.59  5084.2 2167.04
  5105.9 2177.02  5129.3 2182.73  5147.7 2184.74  5170.9 2190.97  5200.7 2205.05
  5206.1 2206.29  5214.3 2212.86  5224.5 2218.21  5229.9 2219.13  5242.3 2230.46
#Mann=4,-1,0
  4627.3    0.07       0  4705.4    0.16       0  5014.4    0.07       0
  5021.3    0.16       0
Bank Sta=5014.4,5021.3
Exp/Cntr=0.3,0.1

Type RM Length L Ch R = 1,8558,208,208,208
BEGIN DESCRIPTION:
Elm 52 8557.568
END DESCRIPTION:
XS GIS Cut Line= 3
      1514255.02      6768887.97      1514486.92      6768619.05
      1514654.99      6768388.01
#Sta/Elev= 30
  4644.9 2200.29  4652.0 2199.51  4658.6 2195.76  4666.2 2193.96  4672.9 2190.08
  4680.5 2188.27  4687.1 2184.16  4694.8 2182.57  4701.4 2178.97  4723.3 2172.43
  4729.9 2169.02  4801.2 2161.94  4840.0 2159.67  4914.2 2158.49  4942.7 2156.90
  4977.8 2147.43  4993.9 2141.13  4994.4 2140.63  5000.8 2141.13  5050.4 2150.05
  5063.1 2158.54  5077.5 2165.27  5113.0 2173.10  5127.7 2177.96  5149.7 2187.23
  5207.3 2222.59  5222.0 2232.39  5242.8 2248.74  5282.6 2276.02  5285.7 2276.02
#Mann=4,-1,0
  4644.9    0.07       0  4840.0    0.16       0  4993.9    0.07       0
  5000.8    0.16       0
Bank Sta=4993.9,5000.8
Exp/Cntr=0.3,0.1

Type RM Length L Ch R = 1,8350,163,163,163
BEGIN DESCRIPTION:
Elm 52 8349.95
END DESCRIPTION:
XS GIS Cut Line= 3
      1514382.86      6768993.57      1514648.48      6768738.37
      1514799.35      6768552.81
#Sta/Elev= 30
  4627.1 2186.95  4646.6 2177.97  4674.9 2169.90  4689.1 2168.00  4767.0 2163.25
  4844.7 2162.34  4862.8 2158.48  4894.1 2153.10  4972.1 2144.38  4979.0 2145.56
  5011.0 2140.49  5011.5 2139.99  5018.0 2140.49  5028.9 2142.84  5049.7 2157.09
  5072.0 2168.68  5092.8 2176.13  5113.6 2179.61  5121.5 2183.99  5142.3 2190.26
  5156.7 2196.18  5171.1 2206.83  5177.5 2208.45  5185.4 2214.13  5191.9 2215.27
  5199.8 2220.67  5206.3 2221.31  5214.2 2226.12  5220.6 2224.73  5234.6 2233.52
#Mann=4,-1,0
  4627.1    0.07       0  4862.8    0.16       0  5011.0    0.07       0
  5018.0    0.16       0
Bank Sta=5011,5018
Exp/Cntr=0.3,0.1

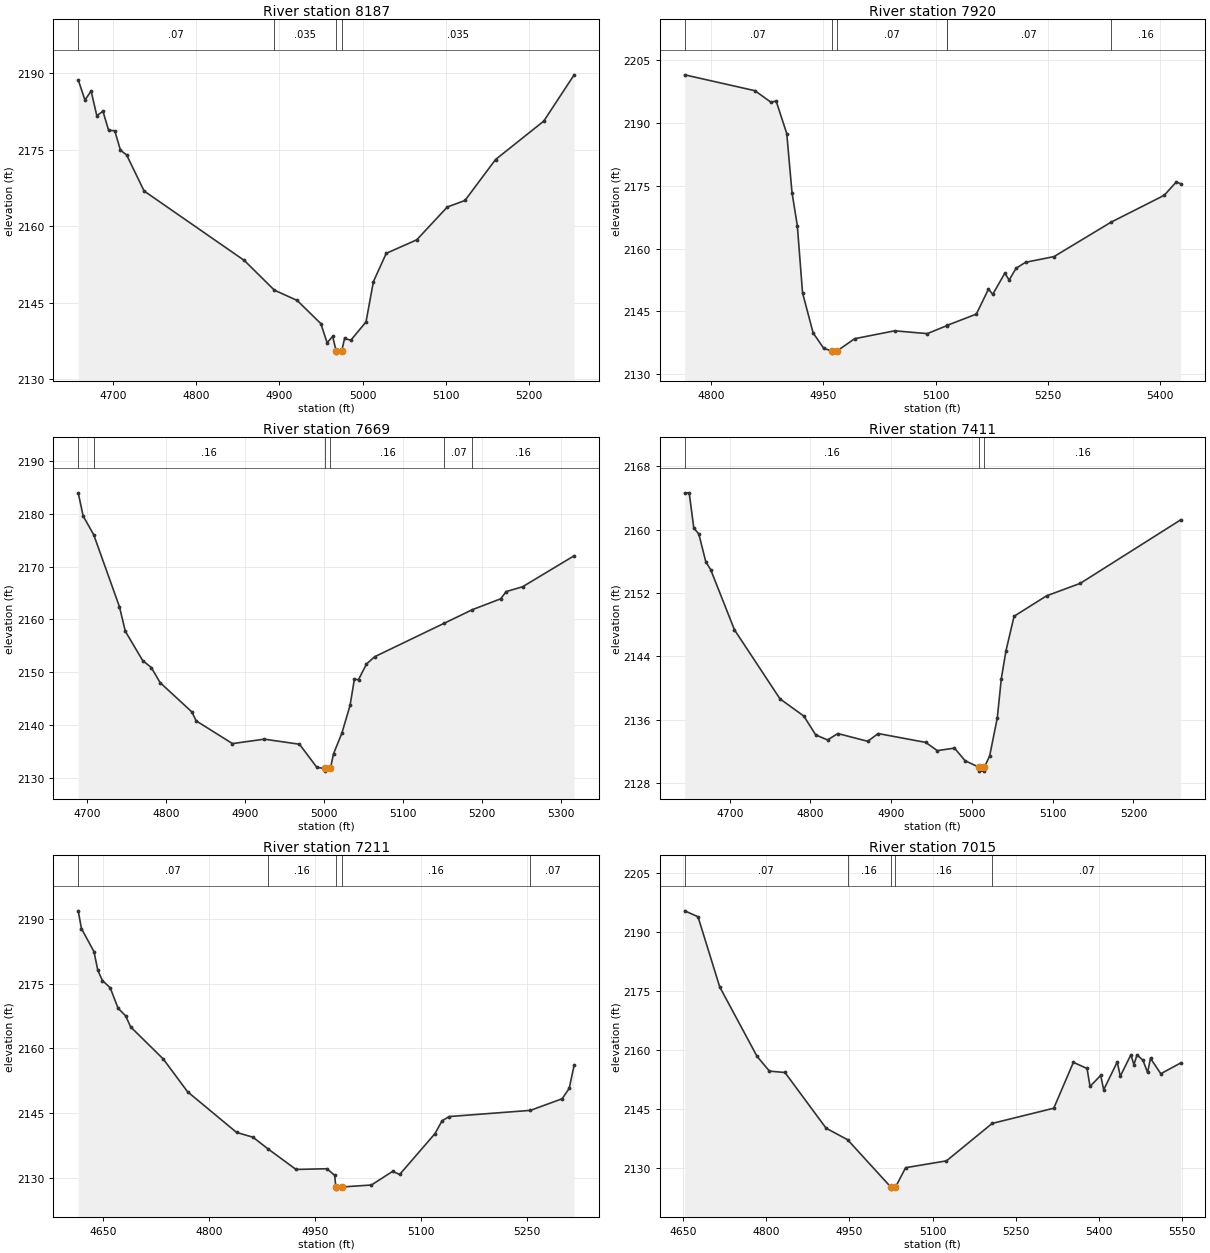
Type RM Length L Ch R = 1,8187,267,267,267
BEGIN DESCRIPTION:
Elm 52 8186.62
END DESCRIPTION:
XS GIS Cut Line= 3
      1514500.91      6769085.59      1514757.86      6768854.69
      1514889.24      6768642.06
#Sta/Elev= 30
  4658.5 2188.67  4666.6 2184.71  4674.0 2186.49  4680.8 2181.65  4688.2 2182.51
  4695.0 2178.78  4702.4 2178.69  4709.2 2174.88  4716.6 2173.96  4737.6 2166.89
  4857.9 2153.28  4894.0 2147.46  4921.4 2145.44  4949.8 2140.90  4957.3 2137.15
  4964.0 2138.41  4968.0 2135.62  4968.5 2135.12  4975.0 2135.62  4978.3 2138.02
  4985.7 2137.64  5004.0 2141.23  5012.9 2149.13  5028.3 2154.67  5064.9 2157.32
  5101.6 2163.75  5122.8 2165.03  5159.5 2173.05  5217.4 2180.58  5253.9 2189.65
#Mann=4,-1,0
  4658.5    0.07       0  4894.0   0.035       0  4968.0   0.035       0
  4975.0   0.035       0
Bank Sta=4968,4975
Exp/Cntr=0.3,0.1

Type RM Length L Ch R = 1,7920,251,251,251
BEGIN DESCRIPTION:
Elm 52 7919.98
END DESCRIPTION:
XS GIS Cut Line= 3
      1514653.67      6769269.64      1514815.15      6769104.69
      1515020.80      6768724.48
#Sta/Elev= 30
  4764.5 2201.55  4858.5 2197.75  4879.7 2195.01  4886.8 2195.28  4901.0 2187.48
  4908.0 2173.39  4915.1 2165.50  4922.1 2149.39  4936.3 2139.78  4950.4 2136.13
  4961.1 2135.47  4961.6 2134.97  4968.1 2135.47  4991.7 2138.42  5045.2 2140.31
  5088.9 2139.64  5114.9 2141.53  5115.4 2141.61  5154.5 2144.31  5170.7 2150.30
  5176.4 2149.04  5192.6 2154.11  5198.3 2152.46  5207.6 2155.27  5220.2 2156.70
  5258.3 2158.06  5334.6 2166.30  5405.7 2172.73  5421.9 2175.94  5427.6 2175.49
#Mann=6,-1,0
  4764.5    0.07       0  4961.1    0.07       0  4968.1    0.07       0
  5114.9    0.16       0  5115.4    0.07       0  5334.6    0.16       0
Bank Sta=4961.1,4968.1
Exp/Cntr=0.3,0.1

Type RM Length L Ch R = 1,7669,258,258,258
BEGIN DESCRIPTION:
Elm 52 7668.66
END DESCRIPTION:
XS GIS Cut Line= 3
      1514908.89      6769372.06      1515039.11      6769090.80
      1515125.92      6768785.23
#Sta/Elev= 30
  4688.9 2183.98  4695.2 2179.57  4708.5 2176.04  4741.1 2162.38  4748.5 2157.74
  4770.5 2152.18  4781.4 2150.86  4792.6 2147.99  4832.7 2142.45  4838.2 2140.75
  4884.1 2136.44  4924.4 2137.28  4968.9 2136.32  4990.9 2131.93  5001.0 2131.72
  5001.5 2131.22  5008.0 2131.72  5012.1 2134.56  5022.5 2138.39  5032.9 2143.67
  5038.4 2148.65  5043.6 2148.56  5053.7 2151.53  5064.1 2152.91  5152.4 2159.28
  5187.6 2161.82  5223.5 2163.89  5230.5 2165.26  5251.2 2166.17  5316.5 2172.05
#Mann=6,-1,0
  4688.9    0.07       0  4708.5    0.16       0  5001.0    0.07       0
  5008.0    0.16       0  5152.4    0.07       0  5187.6    0.16       0
Bank Sta=5001,5008
Exp/Cntr=0.3,0.1

Type RM Length L Ch R = 1,7411,200,200,200
BEGIN DESCRIPTION:
Elm 52 7410.56
END DESCRIPTION:
XS GIS Cut Line= 3
      1514960.98      6769439.76      1515245.70      6769234.90
      1515273.47      6768972.83
#Sta/Elev= 30
  4644.2 2164.65  4649.8 2164.65  4655.5 2160.20  4661.7 2159.45  4670.3 2155.96
  4676.4 2154.94  4705.9 2147.33  4762.3 2138.61  4791.8 2136.44  4806.5 2134.06
  4821.2 2133.42  4833.9 2134.23  4870.9 2133.25  4883.9 2134.23  4942.8 2133.11
  4957.1 2132.07  4978.4 2132.39  4991.5 2130.80  5008.5 2129.98  5009.0 2129.48
  5015.0 2129.48  5015.5 2129.98  5022.0 2131.42  5031.4 2136.20  5036.4 2141.16
  5042.1 2144.66  5052.2 2149.05  5092.4 2151.63  5134.2 2153.21  5258.5 2161.23
#Mann=3,-1,0
  4644.2    0.16       0  5008.5    0.07       0  5015.5    0.16       0
Bank Sta=5008.5,5015.5
Exp/Cntr=0.3,0.1

Type RM Length L Ch R = 1,7211,196,196,196
BEGIN DESCRIPTION:
Elm 52 7210.94
END DESCRIPTION:
XS GIS Cut Line= 3
      1514903.67      6769543.93      1515256.12      6769385.94
      1515571.96      6769382.49
#Sta/Elev= 30
  4614.6 2192.00  4619.2 2187.87  4636.9 2182.52  4642.4 2178.14  4648.9 2175.79
  4659.9 2174.11  4671.1 2169.34  4681.8 2167.58  4688.8 2165.03  4735.1 2157.54
  4769.5 2149.93  4838.8 2140.49  4862.0 2139.38  4882.7 2136.74  4922.9 2131.89
  4966.7 2132.05  4977.7 2130.52  4979.3 2127.81  4979.8 2127.31  4987.5 2127.81
  5029.7 2128.27  5059.7 2131.44  5069.7 2130.72  5119.7 2140.22  5129.7 2143.19
  5139.7 2144.18  5254.9 2145.62  5299.7 2148.32  5309.7 2150.73  5316.7 2156.15
#Mann=5,-1,0
  4614.6    0.07       0  4882.7    0.16       0  4979.3    0.07       0
  4987.5    0.16       0  5254.9    0.07       0
Bank Sta=4979.3,4987.5
Exp/Cntr=0.3,0.1

Type RM Length L Ch R = 1,7015,261,261,261
BEGIN DESCRIPTION:
Elm 52 7015.32
END DESCRIPTION:
XS GIS Cut Line= 3
      1514976.61      6769722.74      1515270.01      6769576.91
      1515798.31      6769372.52
#Sta/Elev= 30
  4653.0 2195.40  4677.0 2193.90  4716.2 2176.05  4783.4 2158.42  4805.8 2154.65
  4833.8 2154.30  4908.0 2140.14  4946.7 2137.21  5024.8 2125.15  5025.3 2124.65
  5033.0 2125.15  5051.3 2130.10  5125.0 2131.84  5207.4 2141.36  5318.4 2145.22
  5353.8 2156.89  5378.4 2155.32  5383.8 2150.75  5403.0 2153.57  5408.4 2149.91
  5432.9 2156.99  5438.3 2153.34  5457.5 2158.82  5462.9 2156.28  5468.5 2158.79
  5479.2 2157.41  5487.5 2154.30  5492.8 2157.90  5511.4 2153.99  5547.1 2156.72
#Mann=5,-1,0
  4653.0    0.07       0  4946.7    0.16       0  5024.8    0.07       0
  5033.0    0.16       0  5207.4    0.07       0
Bank Sta=5024.8,5033
Exp/Cntr=0.3,0.1

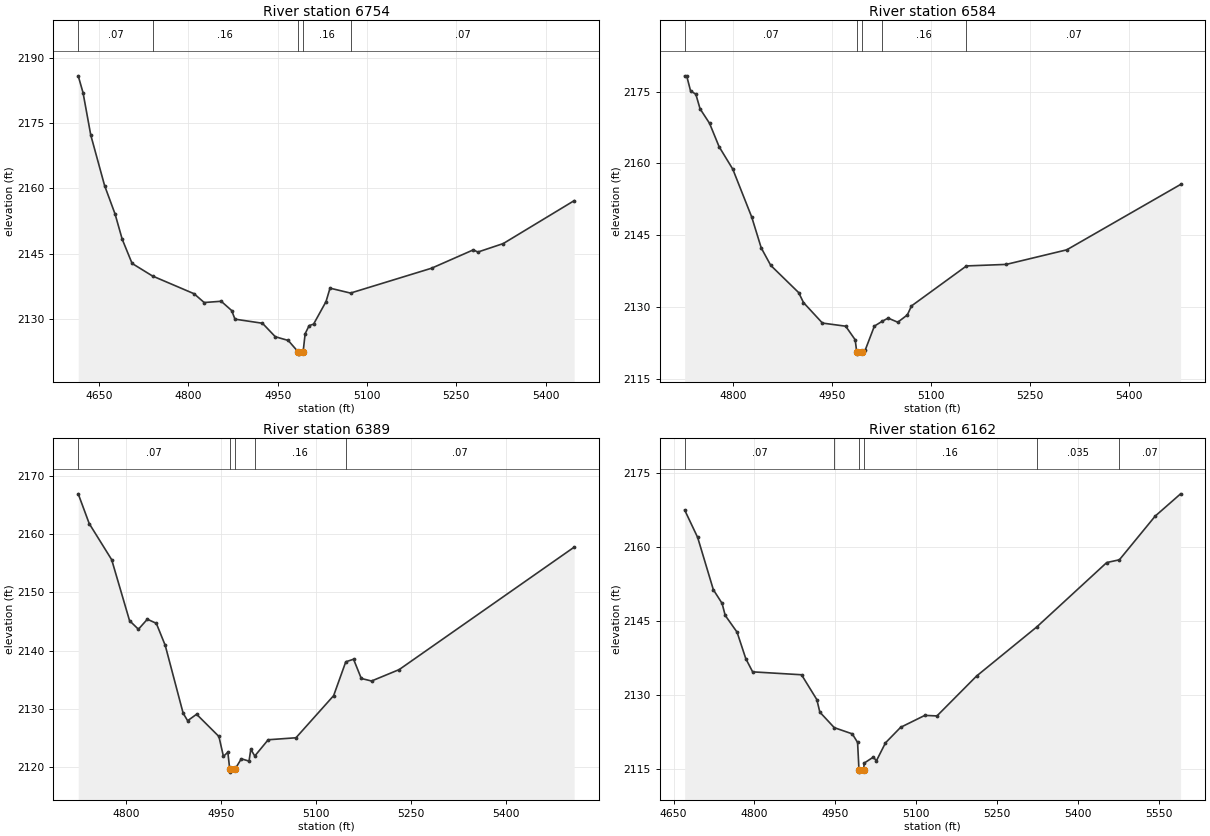
Type RM Length L Ch R = 1,6754,170,170,170
BEGIN DESCRIPTION:
Elm 52 6754.06
END DESCRIPTION:
XS GIS Cut Line= 3
      1515167.62      6769870.30      1515455.77      6769740.10
      1515841.44      6769395.95
#Sta/Elev= 30
  4615.0 2185.81  4623.1 2181.94  4636.1 2172.20  4659.3 2160.61  4676.9 2154.08
  4688.9 2148.29  4705.5 2142.73  4739.8 2139.84  4809.6 2135.77  4826.6 2133.75
  4855.2 2134.04  4872.8 2131.91  4878.3 2129.93  4924.5 2128.99  4946.1 2125.89
  4967.8 2125.04  4984.6 2122.40  4985.1 2121.90  4992.8 2122.40  4996.2 2126.58
  5002.9 2128.45  5010.4 2128.79  5031.3 2133.97  5038.0 2137.05  5072.4 2135.92
  5208.6 2141.63  5278.8 2145.85  5286.3 2145.34  5329.0 2147.29  5448.1 2157.14
#Mann=5,-1,0
  4615.0    0.07       0  4739.8    0.16       0  4984.6    0.07       0
  4992.8    0.16       0  5072.4    0.07       0
Bank Sta=4984.6,4992.8
Exp/Cntr=0.3,0.1

Type RM Length L Ch R = 1,6584,195,195,195
BEGIN DESCRIPTION:
Elm 52 6583.94
END DESCRIPTION:
XS GIS Cut Line= 3
      1515426.23      6770042.22      1515596.40      6769832.12
      1515886.34      6769448.42
#Sta/Elev= 30
  4726.8 2178.28  4729.8 2178.28  4735.7 2175.15  4743.7 2174.44  4750.1 2171.40
  4764.5 2168.36  4778.9 2163.50  4799.7 2158.79  4828.4 2148.79  4842.8 2142.35
  4857.2 2138.71  4899.5 2133.03  4906.8 2130.95  4935.5 2126.67  4970.7 2126.02
  4985.1 2123.18  4987.4 2120.69  4987.9 2120.19  4995.6 2120.69  5000.2 2121.00
  5014.2 2126.04  5025.7 2127.02  5035.0 2127.71  5049.6 2126.85  5064.1 2128.37
  5070.4 2130.25  5153.7 2138.60  5214.0 2138.92  5305.6 2141.96  5478.1 2155.61
#Mann=5,-1,0
  4726.8    0.07       0  4987.4    0.07       0  4995.6    0.07       0
  5025.7    0.16       0  5153.7    0.07       0
Bank Sta=4987.4,4995.6
Exp/Cntr=0.3,0.1

Type RM Length L Ch R = 1,6389,227,227,227
BEGIN DESCRIPTION:
Elm 52 6388.91
END DESCRIPTION:
XS GIS Cut Line= 3
      1515558.23      6770135.91      1515747.44      6769943.23
      1515993.16      6769491.60
#Sta/Elev= 30
  4724.1 2166.91  4741.5 2161.80  4777.0 2155.60  4805.3 2145.12  4819.3 2143.65
  4833.4 2145.37  4847.6 2144.67  4861.7 2140.88  4890.0 2129.24  4897.1 2127.94
  4911.3 2129.05  4946.6 2125.23  4953.7 2121.82  4960.7 2122.52  4963.7 2119.61
  4964.2 2119.11  4972.0 2119.61  4982.0 2121.40  4994.2 2121.00  4997.0 2123.02
  5003.3 2121.88  5024.5 2124.67  5068.4 2125.01  5128.0 2132.25  5147.2 2138.06
  5159.5 2138.50  5171.7 2135.20  5187.9 2134.76  5231.6 2136.72  5508.3 2157.75
#Mann=5,-1,0
  4724.1    0.07       0  4963.7    0.07       0  4972.0    0.07       0
  5003.3    0.16       0  5147.2    0.07       0
Bank Sta=4963.7,4972
Exp/Cntr=0.3,0.1

Type RM Length L Ch R = 1,6162,232,232,232
BEGIN DESCRIPTION:
Elm 52 6162.18
END DESCRIPTION:
XS GIS Cut Line= 3
      1515613.74      6770198.45      1515896.75      6770047.40
      1516434.94      6769783.51
#Sta/Elev= 30
  4670.7 2167.49  4694.8 2161.93  4723.9 2151.33  4740.1 2148.56  4745.9 2146.12
  4767.9 2142.72  4784.1 2137.34  4796.8 2134.67  4887.5 2134.08  4915.9 2129.04
  4921.5 2126.50  4948.3 2123.35  4981.7 2122.09  4991.5 2120.36  4994.1 2114.83
  4994.6 2114.33  5002.6 2114.83  5003.9 2116.17  5020.8 2117.38  5026.4 2116.62
  5043.3 2120.27  5071.4 2123.42  5116.3 2125.84  5138.8 2125.73  5212.3 2133.82
  5324.0 2143.78  5453.8 2156.84  5477.3 2157.40  5543.7 2166.26  5590.9 2170.78
#Mann=6,-1,0
  4670.7    0.07       0  4948.3    0.16       0  4994.1    0.07       0
  5002.6    0.16       0  5324.0   0.035       0  5477.3    0.07       0
Bank Sta=4994.1,5002.6
Exp/Cntr=0.3,0.1