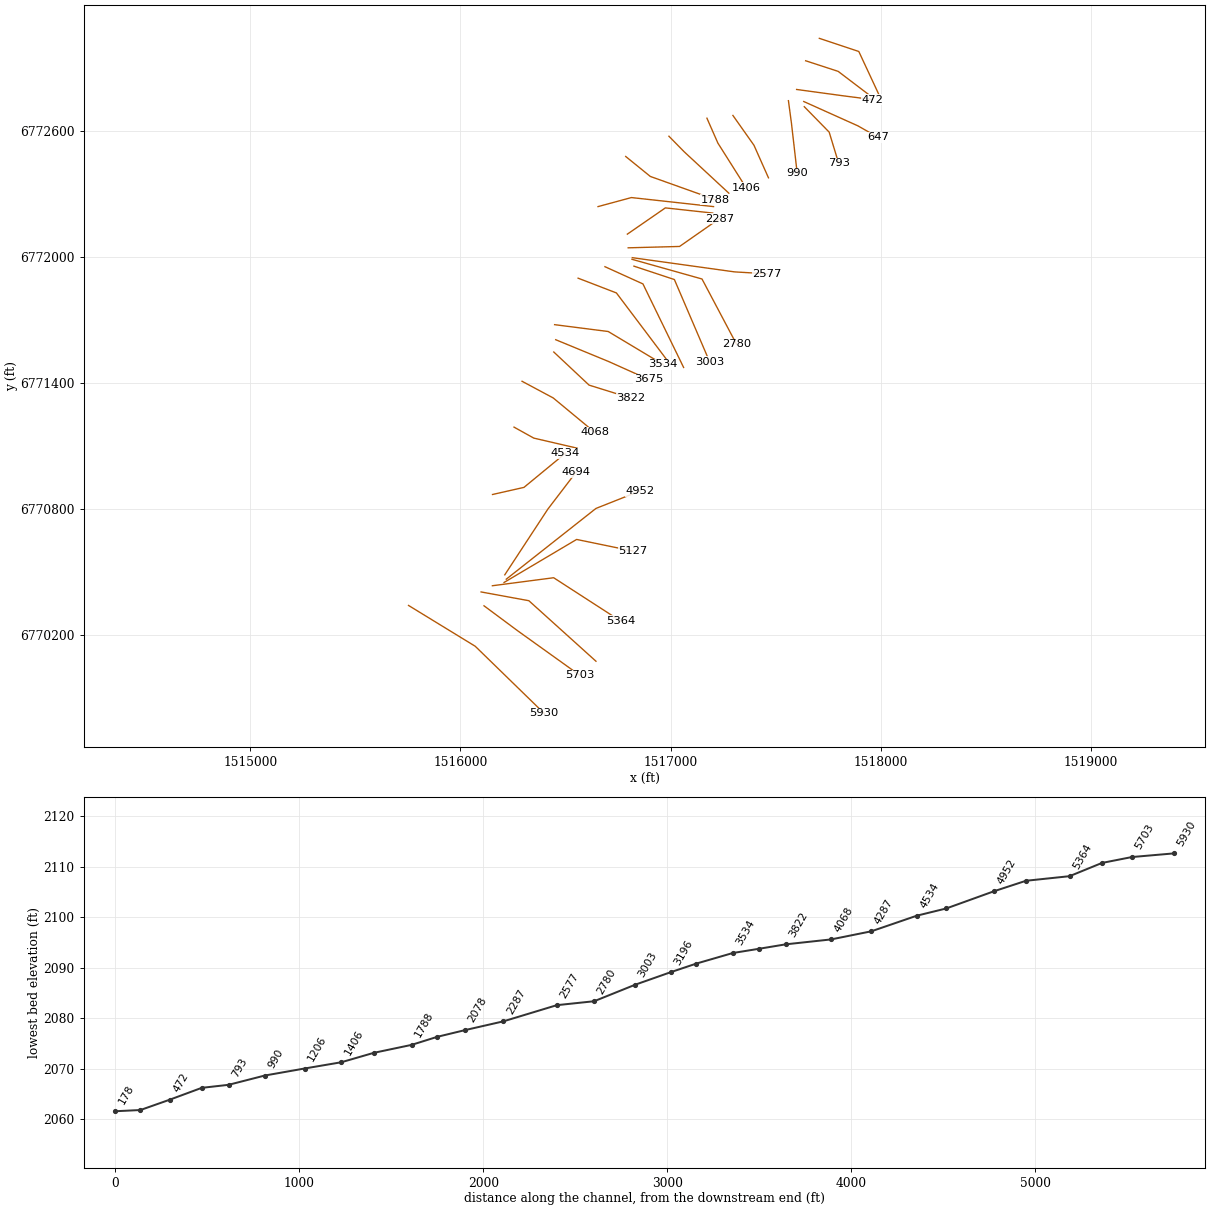
HEC-RAS study Elm 52.prj: Elm 52 Base Level Engineering

--- Elm 52.g01 (geometry) --- (continued)

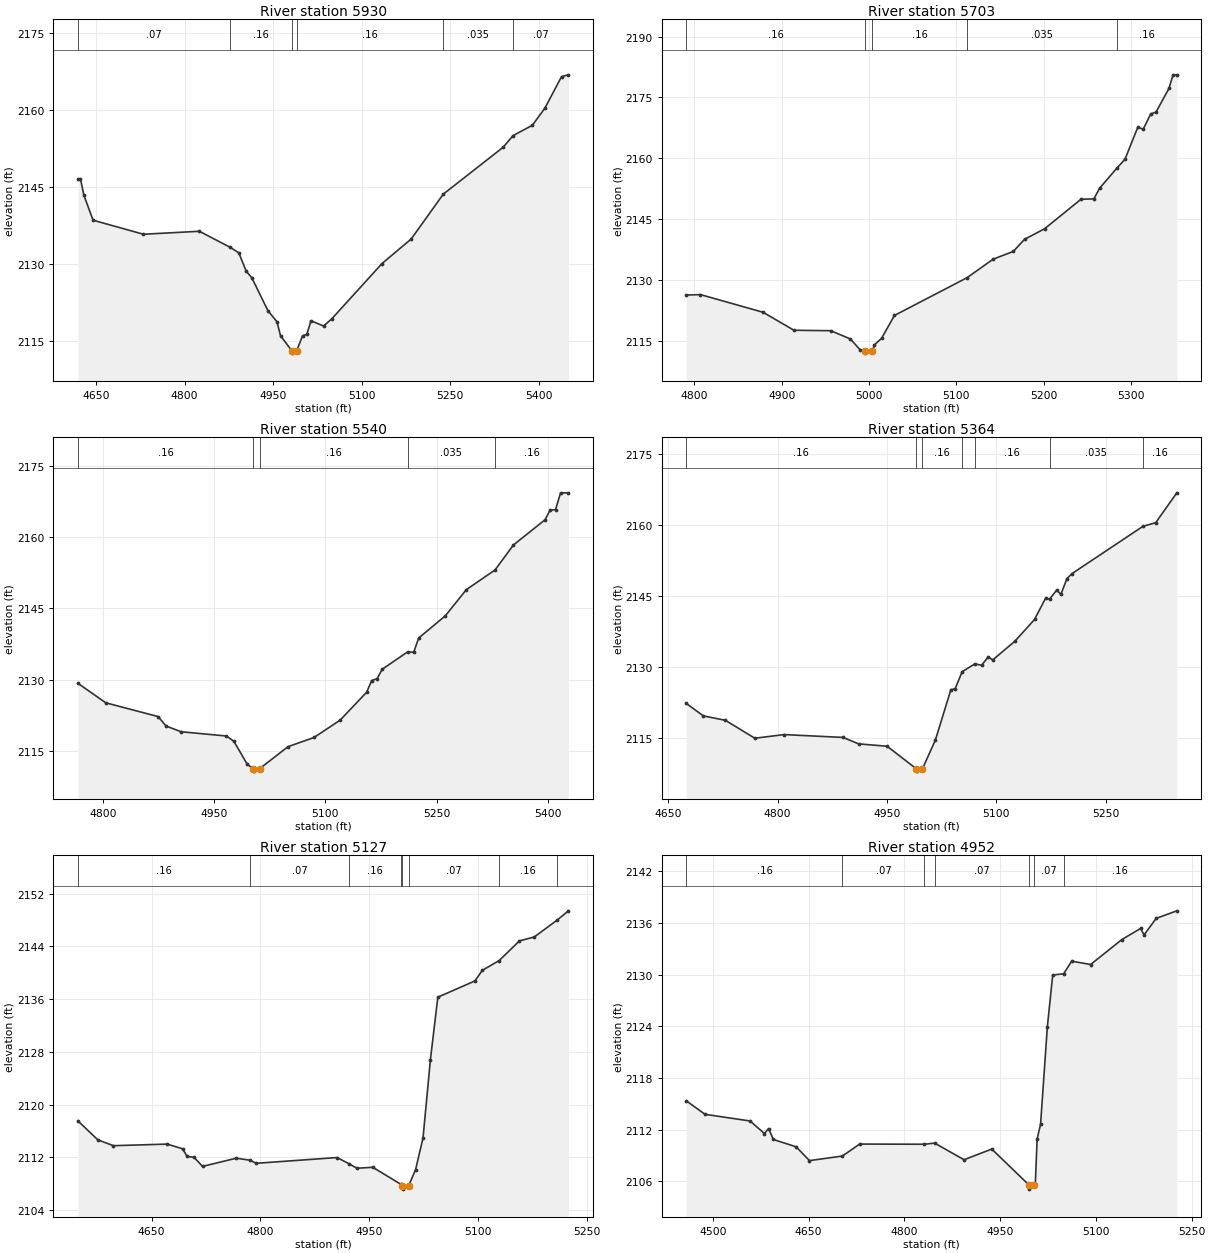
Type RM Length L Ch R = 1,5930,227,227,227
BEGIN DESCRIPTION:
Elm 52 5930.29
END DESCRIPTION:
XS GIS Cut Line= 3
      1515752.62      6770339.08      1516070.36      6770144.62
      1516398.51      6769825.15
#Sta/Elev= 30
  4619.5 2146.58  4623.8 2146.58  4629.6 2143.41  4645.1 2138.54  4730.3 2135.80
  4825.1 2136.38  4876.8 2133.28  4891.9 2132.19  4904.4 2128.60  4914.0 2127.30
  4941.2 2120.89  4956.6 2118.72  4962.5 2116.01  4981.5 2113.11  4982.0 2112.61
  4990.0 2113.11  4999.9 2115.99  5007.1 2116.27  5014.1 2118.93  5035.4 2117.90
  5049.5 2119.32  5134.4 2130.09  5183.8 2134.87  5238.1 2143.62  5339.4 2152.76
  5356.3 2155.04  5389.0 2157.06  5410.1 2160.38  5438.4 2166.55  5450.0 2166.90
#Mann=6,-1,0
  4619.5    0.07       0  4876.8    0.16       0  4981.5    0.07       0
  4990.0    0.16       0  5238.1   0.035       0  5356.3    0.07       0
Bank Sta=4981.5,4990
Exp/Cntr=0.3,0.1

Type RM Length L Ch R = 1,5703,163,163,163
BEGIN DESCRIPTION:
Elm 52 5702.66
END DESCRIPTION:
XS GIS Cut Line= 3
      1516112.06      6770337.30      1516273.48      6770217.53
      1516566.92      6770007.44
#Sta/Elev= 30
  4790.7 2126.22  4806.8 2126.33  4878.6 2121.97  4914.0 2117.53  4956.2 2117.42
  4978.7 2115.37  4989.5 2112.77  4995.4 2112.39  4995.9 2111.89  5003.9 2112.39
  5005.9 2113.88  5014.3 2115.53  5029.1 2121.19  5112.1 2130.48  5142.1 2135.06
  5165.4 2137.00  5178.1 2139.97  5201.1 2142.57  5242.8 2149.85  5257.6 2149.95
  5264.1 2152.57  5283.7 2157.47  5293.2 2159.72  5307.9 2167.63  5314.1 2167.15
  5322.7 2170.89  5328.8 2171.37  5343.6 2177.20  5348.3 2180.55  5352.6 2180.55
#Mann=5,-1,0
  4790.7    0.16       0  4995.4    0.07       0  5003.9    0.16       0
  5112.1   0.035       0  5283.7    0.16       0
Bank Sta=4995.4,5003.9
Exp/Cntr=0.3,0.1

Type RM Length L Ch R = 1,5540,176,176,176
BEGIN DESCRIPTION:
Elm 52 5540.19
END DESCRIPTION:
XS GIS Cut Line= 3
      1516098.12      6770403.30      1516325.57      6770361.63
      1516645.04      6770073.41
#Sta/Elev= 30
  4766.2 2129.23  4803.7 2125.12  4874.3 2122.22  4885.0 2120.23  4905.4 2119.02
  4966.4 2118.12  4976.5 2117.01  4994.6 2112.15  5002.6 2111.22  5003.1 2110.72
  5011.1 2111.22  5049.5 2115.87  5084.6 2117.81  5119.7 2121.45  5155.6 2127.35
  5162.3 2129.79  5169.8 2130.23  5176.5 2132.18  5210.7 2135.84  5219.1 2135.78
  5225.8 2138.78  5261.7 2143.46  5290.1 2148.98  5328.7 2153.11  5353.6 2158.39
  5396.2 2163.70  5403.0 2165.73  5410.4 2165.84  5417.1 2169.36  5427.7 2169.38
#Mann=5,-1,0
  4766.2    0.16       0  5002.6    0.07       0  5011.1    0.16       0
  5210.7   0.035       0  5328.7    0.16       0
Bank Sta=5002.6,5011.1
Exp/Cntr=0.3,0.1

Type RM Length L Ch R = 1,5364,237,237,237
BEGIN DESCRIPTION:
Elm 52 5363.65
END DESCRIPTION:
XS GIS Cut Line= 3
      1516151.91      6770432.81      1516443.62      6770471.01
      1516761.53      6770265.40
#Sta/Elev= 30
  4674.8 2122.39  4698.1 2119.77  4728.3 2118.84  4768.7 2115.05  4809.0 2115.82
  4889.7 2115.22  4911.1 2113.86  4950.2 2113.36  4990.2 2108.60  4990.7 2108.10
  4998.7 2108.60  5016.5 2114.71  5037.6 2125.29  5043.5 2125.50  5053.1 2129.11
  5070.5 2130.75  5079.8 2130.47  5089.0 2132.25  5095.0 2131.59  5125.3 2135.52
  5152.4 2140.14  5167.5 2144.61  5173.1 2144.45  5182.7 2146.33  5188.6 2145.48
  5196.9 2148.78  5203.8 2149.83  5301.3 2159.84  5318.6 2160.58  5347.6 2166.90
#Mann=7,-1,0
  4674.8    0.16       0  4990.2    0.07       0  4998.7    0.16       0
  5053.1    0.07       0  5070.5    0.16       0  5173.1   0.035       0
  5301.3    0.16       0
Bank Sta=4990.2,4998.7
Exp/Cntr=0.3,0.1

Type RM Length L Ch R = 1,5127,175,175,175
BEGIN DESCRIPTION:
Elm 52 5126.65
END DESCRIPTION:
XS GIS Cut Line= 3
      1516207.47      6770448.42      1516553.00      6770653.30
      1516821.04      6770597.96
#Sta/Elev= 30
  4548.7 2117.54  4576.1 2114.67  4597.5 2113.78  4671.6 2114.02  4693.0 2113.30
  4698.9 2112.16  4708.6 2112.01  4720.3 2110.64  4766.7 2111.88  4785.5 2111.58
  4794.4 2111.11  4905.5 2111.98  4921.7 2111.06  4932.8 2110.36  4954.7 2110.50
  4993.2 2107.94  4995.6 2107.69  4996.1 2107.19  5004.1 2107.69  5013.7 2110.16
  5023.9 2114.95  5034.1 2126.85  5044.3 2136.31  5095.3 2138.77  5105.6 2140.38
  5128.8 2141.87  5156.7 2144.85  5177.1 2145.44  5208.9 2148.03  5224.1 2149.41
#Mann=8,-1,0
  4548.7    0.16       0  4785.5    0.07       0  4921.7    0.16       0
  4993.2    0.07       0  4995.6    0.07       0  5004.1    0.07       0
  5128.8    0.16       0  5208.9   0.035       0
Bank Sta=4995.6,5004.1
Exp/Cntr=0.3,0.1

Type RM Length L Ch R = 1,4952,258,258,258
BEGIN DESCRIPTION:
Elm 52 4951.93
END DESCRIPTION:
XS GIS Cut Line= 3
      1516217.96      6770464.09      1516645.01      6770800.87
      1516853.54      6770883.59
#Sta/Elev= 30
  4458.5 2115.34  4487.8 2113.78  4558.3 2113.01  4580.8 2111.55  4587.2 2112.13
  4594.8 2110.86  4630.5 2110.01  4651.3 2108.41  4702.9 2108.94  4729.9 2110.33
  4831.3 2110.31  4847.4 2110.44  4893.4 2108.51  4936.8 2109.75  4994.9 2105.60
  4995.4 2105.10  5003.5 2105.60  5005.0 2105.60  5007.9 2110.91  5013.3 2112.64
  5023.9 2123.93  5032.3 2129.95  5049.4 2130.09  5062.0 2131.56  5091.7 2131.17
  5140.3 2134.05  5170.0 2135.36  5175.4 2134.60  5194.3 2136.52  5226.7 2137.40
#Mann=7,-1,0
  4458.5    0.16       0  4702.9    0.07       0  4831.3    0.16       0
  4847.4    0.07       0  4994.9    0.07       0  5003.5    0.07       0
  5049.4    0.16       0
Bank Sta=4994.9,5003.5
Exp/Cntr=0.3,0.1

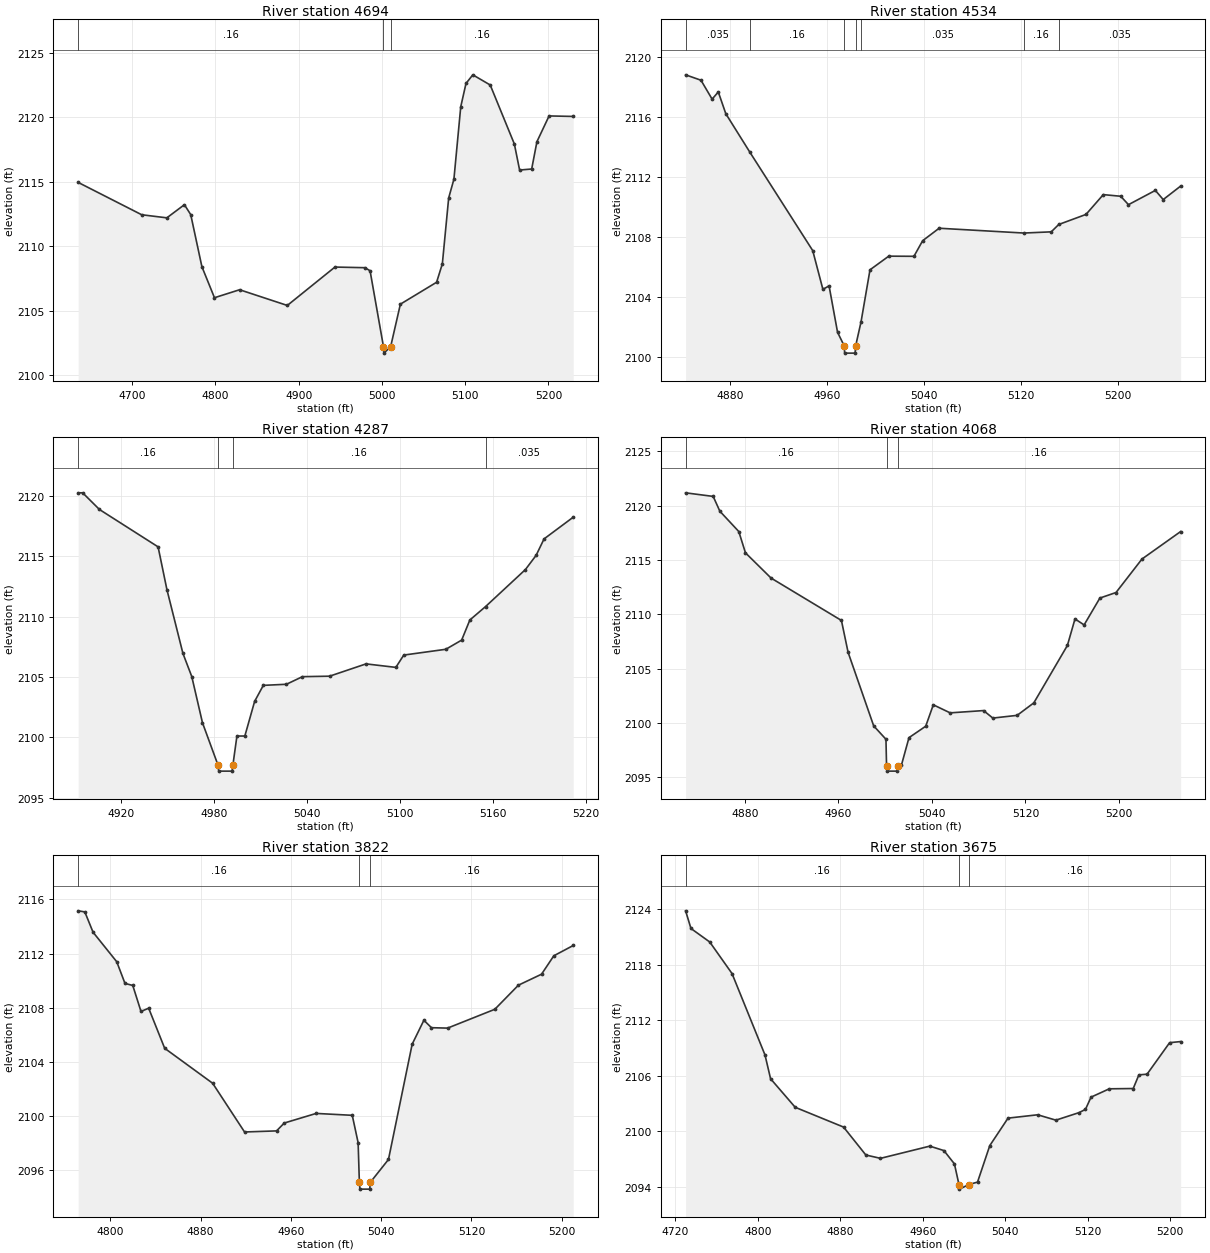
Type RM Length L Ch R = 1,4694,160,160,160
BEGIN DESCRIPTION:
Elm 52 4694.03
END DESCRIPTION:
XS GIS Cut Line= 3
      1516210.99      6770484.91      1516415.84      6770797.40
      1516550.06      6770972.91
#Sta/Elev= 30
  4635.2 2114.96  4711.5 2112.45  4741.7 2112.21  4762.8 2113.23  4770.4 2112.46
  4783.8 2108.42  4798.9 2106.01  4829.1 2106.63  4886.4 2105.41  4943.6 2108.39
  4979.8 2108.34  4985.8 2108.10  5001.9 2102.21  5002.4 2101.71  5010.5 2102.21
  5022.2 2105.51  5065.7 2107.21  5072.6 2108.64  5080.2 2113.75  5086.5 2115.21
  5094.7 2120.83  5101.0 2122.64  5109.2 2123.31  5130.1 2122.52  5159.1 2117.94
  5165.4 2115.92  5179.9 2116.00  5186.2 2118.12  5200.8 2120.12  5229.8 2120.08
#Mann=3,-1,0
  4635.2    0.16       0  5001.9    0.07       0  5010.5    0.16       0
Bank Sta=5001.9,5010.5
Exp/Cntr=0.3,0.1

Type RM Length L Ch R = 1,4534,247,247,247
BEGIN DESCRIPTION:
Elm 52 4533.81
END DESCRIPTION:
XS GIS Cut Line= 3
      1516152.61      6770867.28      1516302.34      6770901.13
      1516499.48      6771063.48
#Sta/Elev= 30
  4843.1 2118.82  4855.8 2118.46  4865.0 2117.20  4870.1 2117.68  4876.3 2116.23
  4896.3 2113.65  4948.1 2107.11  4956.5 2104.53  4961.6 2104.76  4968.6 2101.67
  4974.0 2100.78  4974.5 2100.28  4983.1 2100.28  4983.6 2100.78  4988.0 2102.36
  4995.4 2105.83  5010.9 2106.74  5031.7 2106.73  5038.9 2107.77  5052.5 2108.60
  5122.5 2108.28  5145.1 2108.36  5151.3 2108.85  5173.8 2109.52  5188.1 2110.84
  5202.5 2110.73  5208.9 2110.17  5231.1 2111.12  5237.6 2110.51  5252.0 2111.41
#Mann=7,-1,0
  4843.1   0.035       0  4896.3    0.16       0  4974.0   0.035       0
  4983.6    0.16       0  4988.0   0.035       0  5122.5    0.16       0
  5151.3   0.035       0
Bank Sta=4974,4983.6
Exp/Cntr=0.3,0.1

Type RM Length L Ch R = 1,4287,219,219,219
BEGIN DESCRIPTION:
Elm 52 4286.595
END DESCRIPTION:
XS GIS Cut Line= 3
      1516255.01      6771188.00      1516348.88      6771135.82
      1516555.01      6771088.00
#Sta/Elev= 30
  4892.6 2120.26  4895.5 2120.26  4906.3 2118.88  4944.1 2115.78  4949.8 2112.23
  4960.1 2106.95  4965.8 2105.03  4972.7 2101.20  4982.7 2097.69  4983.2 2097.19
  4991.8 2097.19  4992.3 2097.69  4994.9 2100.10  5000.0 2100.10  5006.3 2102.97
  5011.9 2104.30  5026.8 2104.39  5037.1 2105.02  5054.6 2105.06  5078.1 2106.08
  5097.3 2105.79  5102.4 2106.81  5129.5 2107.29  5139.7 2108.05  5145.0 2109.72
  5155.1 2110.83  5180.8 2113.90  5187.7 2115.08  5192.8 2116.44  5211.6 2118.24
#Mann=4,-1,0
  4892.6    0.16       0  4982.7    0.07       0  4992.3    0.16       0
  5155.1   0.035       0
Bank Sta=4982.7,4992.3
Exp/Cntr=0.3,0.1

Type RM Length L Ch R = 1,4068,246,246,246
BEGIN DESCRIPTION:
Elm 52 4067.56
END DESCRIPTION:
XS GIS Cut Line= 3
      1516293.27      6771406.31      1516441.67      6771326.91
      1516638.25      6771164.18
#Sta/Elev= 30
  4829.3 2121.18  4852.9 2120.85  4858.6 2119.49  4874.8 2117.62  4880.5 2115.66
  4902.4 2113.34  4962.6 2109.44  4968.3 2106.51  4990.2 2099.74  5000.7 2098.51
  5001.2 2096.08  5001.7 2095.58  5010.4 2095.58  5010.9 2096.08  5013.9 2096.12
  5020.4 2098.66  5034.7 2099.71  5041.2 2101.68  5055.6 2100.94  5084.2 2101.15
  5092.1 2100.46  5112.9 2100.71  5127.2 2101.86  5155.9 2107.14  5162.4 2109.58
  5170.2 2109.03  5183.7 2111.50  5197.5 2112.01  5219.7 2115.09  5252.8 2117.62
#Mann=3,-1,0
  4829.3    0.16       0  5001.2    0.07       0  5010.9    0.16       0
Bank Sta=5001.2,5010.9
Exp/Cntr=0.3,0.1

Type RM Length L Ch R = 1,3822,147,147,147
BEGIN DESCRIPTION:
Elm 52 3822
END DESCRIPTION:
XS GIS Cut Line= 3
      1516444.26      6771545.67      1516612.24      6771388.11
      1516811.37      6771326.04
#Sta/Elev= 30
  4771.4 2115.16  4777.3 2115.08  4784.6 2113.58  4805.6 2111.40  4812.9 2109.80
  4819.8 2109.65  4827.1 2107.73  4833.9 2107.97  4848.1 2105.01  4890.6 2102.43
  4918.9 2098.83  4947.3 2098.91  4954.1 2099.49  4982.4 2100.20  5014.4 2100.06
  5019.6 2098.04  5020.7 2095.11  5021.2 2094.61  5029.9 2094.61  5030.4 2095.11
  5046.5 2096.80  5067.5 2105.31  5077.9 2107.08  5084.6 2106.53  5098.9 2106.50
  5140.8 2107.89  5161.7 2109.67  5182.2 2110.48  5193.1 2111.84  5210.3 2112.60
#Mann=3,-1,0
  4771.4    0.16       0  5020.7    0.07       0  5030.4    0.16       0
Bank Sta=5020.7,5030.4
Exp/Cntr=0.3,0.1

Type RM Length L Ch R = 1,3675,141,141,141
BEGIN DESCRIPTION:
Elm 52 3674.63
END DESCRIPTION:
XS GIS Cut Line= 3
      1516453.41      6771604.24      1516705.99      6771500.09
      1516894.77      6771415.46
#Sta/Elev= 30
  4729.9 2123.82  4735.1 2121.91  4753.3 2120.45  4774.9 2117.04  4806.9 2108.23
  4812.3 2105.66  4836.2 2102.57  4883.1 2100.43  4904.7 2097.41  4918.9 2097.05
  4966.7 2098.37  4980.4 2097.89  4990.6 2096.45  4995.0 2094.22  4995.5 2093.72
  5004.7 2094.22  5013.0 2094.48  5024.9 2098.43  5042.6 2101.40  5071.3 2101.76
  5089.0 2101.18  5111.6 2102.00  5117.7 2102.35  5123.1 2103.67  5140.8 2104.57
  5164.0 2104.60  5169.5 2106.08  5177.4 2106.15  5199.3 2109.56  5210.0 2109.68
#Mann=3,-1,0
  4729.9    0.16       0  4995.0    0.07       0  5004.7    0.16       0
Bank Sta=4995,5004.7
Exp/Cntr=0.3,0.1

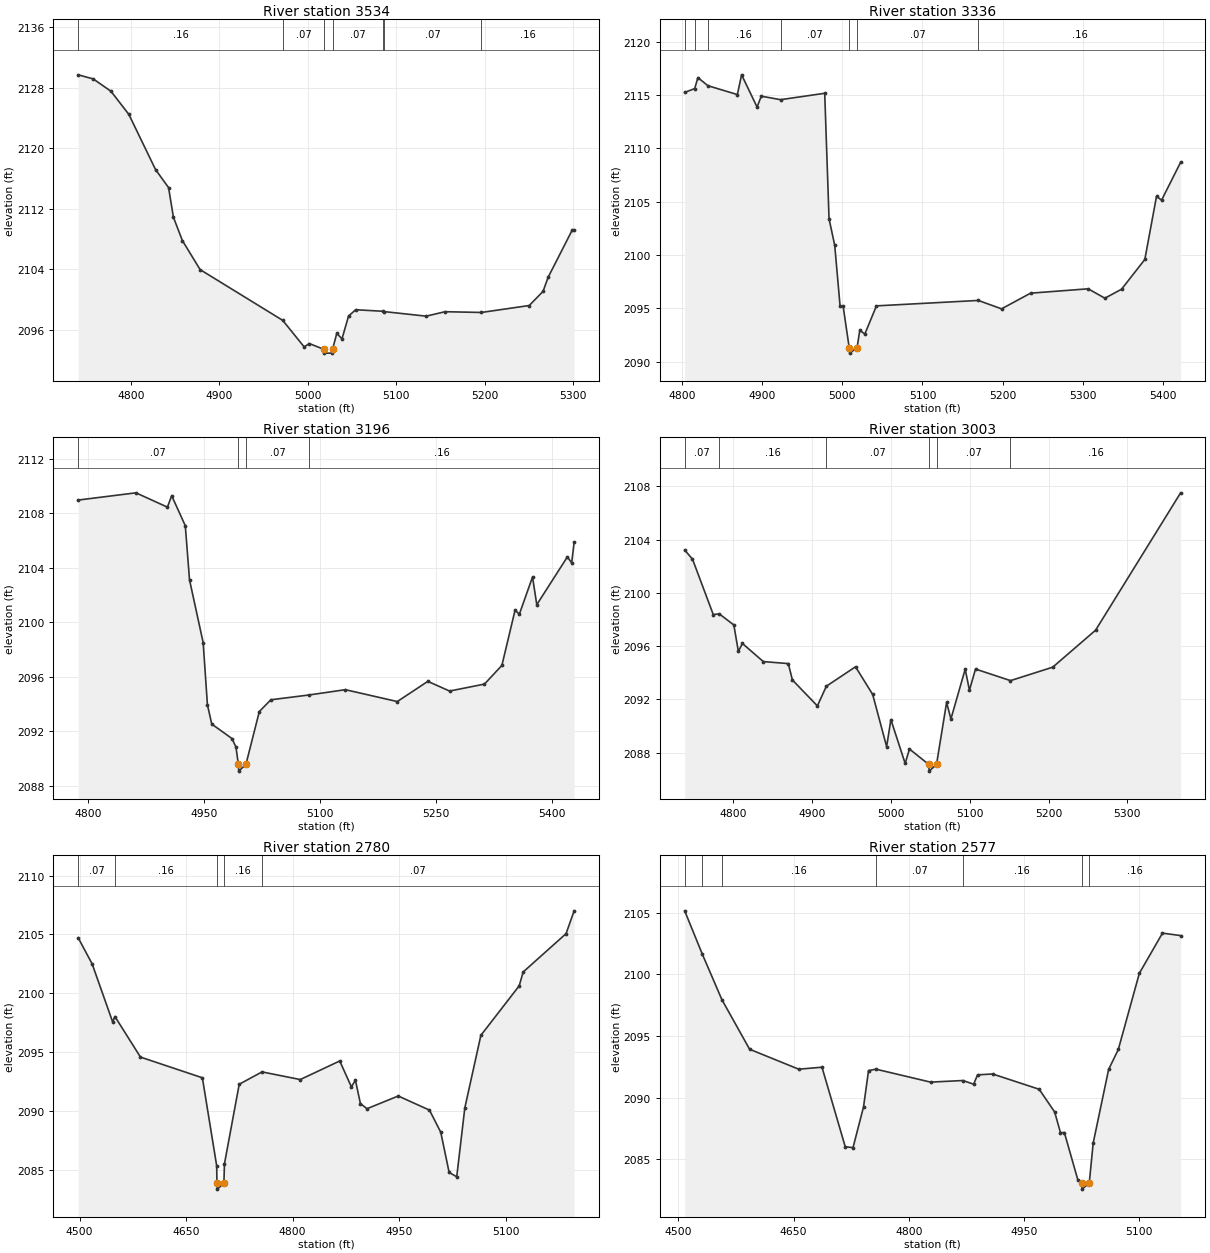
Type RM Length L Ch R = 1,3534,198,198,198
BEGIN DESCRIPTION:
Elm 52 3533.62
END DESCRIPTION:
XS GIS Cut Line= 3
      1516448.18      6771675.87      1516703.39      6771643.32
      1516963.83      6771487.05
#Sta/Elev= 30
  4740.4 2129.71  4757.4 2129.17  4777.5 2127.53  4797.7 2124.47  4827.9 2117.17
  4842.6 2114.79  4848.1 2110.87  4858.2 2107.79  4878.3 2103.94  4971.8 2097.22
  4996.0 2093.71  5001.8 2094.16  5018.3 2093.39  5018.8 2092.89  5027.6 2092.89
  5028.1 2093.39  5032.9 2095.51  5038.8 2094.78  5046.2 2097.80  5054.3 2098.63
  5084.9 2098.43  5086.0 2098.39  5134.0 2097.78  5155.4 2098.37  5196.4 2098.27
  5250.6 2099.19  5266.2 2101.06  5272.0 2102.93  5299.2 2109.17  5301.4 2109.17
#Mann=7,-1,0
  4740.4    0.16       0  4971.8    0.07       0  5018.3    0.07       0
  5028.1    0.07       0  5084.9    0.16       0  5086.0    0.07       0
  5196.4    0.16       0
Bank Sta=5018.3,5028.1
Exp/Cntr=0.3,0.1

Type RM Length L Ch R = 1,3336,140,140,140
BEGIN DESCRIPTION:
Elm 52 3336.14
END DESCRIPTION:
XS GIS Cut Line= 3
      1516560.12      6771897.24      1516742.45      6771826.91
      1516997.67      6771488.35
#Sta/Elev= 30
  4803.0 2115.24  4815.5 2115.60  4819.5 2116.63  4832.0 2115.87  4868.8 2115.04
  4874.1 2116.89  4893.4 2113.87  4898.7 2114.89  4922.7 2114.56  4977.9 2115.16
  4983.3 2103.39  4990.4 2100.91  4997.1 2095.20  5000.9 2095.20  5008.5 2091.30
  5009.0 2090.80  5018.3 2091.30  5021.7 2092.94  5028.0 2092.59  5042.5 2095.23
  5169.8 2095.74  5198.7 2094.95  5235.0 2096.42  5306.9 2096.83  5327.8 2095.95
  5348.6 2096.79  5377.7 2099.58  5392.3 2105.50  5398.6 2105.14  5422.4 2108.69
#Mann=7,-1,0
  4803.0    0.16       0  4815.5    0.07       0  4832.0    0.16       0
  4922.7    0.07       0  5008.5    0.07       0  5018.3    0.07       0
  5169.8    0.16       0
Bank Sta=5008.5,5018.3
Exp/Cntr=0.3,0.1

Type RM Length L Ch R = 1,3196,193,193,193
BEGIN DESCRIPTION:
Elm 52 3196.27
END DESCRIPTION:
XS GIS Cut Line= 3
      1516687.81      6771951.89      1516868.75      6771869.88
      1517062.40      6771472.18
#Sta/Elev= 30
  4787.6 2108.96  4862.2 2109.49  4902.9 2108.44  4908.4 2109.28  4926.0 2107.08
  4931.5 2103.10  4949.1 2098.51  4954.6 2093.96  4960.2 2092.54  4986.3 2091.48
  4991.5 2090.85  4994.6 2089.59  4995.1 2089.09  5004.4 2089.59  5021.7 2093.46
  5036.6 2094.32  5085.6 2094.67  5132.9 2095.06  5200.0 2094.19  5239.5 2095.67
  5267.6 2094.96  5312.7 2095.47  5335.2 2096.84  5352.2 2100.88  5357.8 2100.60
  5374.8 2103.32  5380.3 2101.29  5419.8 2104.79  5425.4 2104.36  5428.6 2105.87
#Mann=4,-1,0
  4787.6    0.07       0  4994.6    0.07       0  5004.4    0.07       0
  5085.6    0.16       0
Bank Sta=4994.6,5004.4
Exp/Cntr=0.3,0.1

Type RM Length L Ch R = 1,3003,223,223,223
BEGIN DESCRIPTION:
Elm 52 3003.48
END DESCRIPTION:
XS GIS Cut Line= 3
      1516825.78      6771954.52      1517018.49      6771890.71
      1517186.46      6771498.79
#Sta/Elev= 30
  4738.2 2103.22  4748.1 2102.54  4774.5 2098.37  4782.0 2098.43  4800.6 2097.59
  4806.3 2095.61  4811.5 2096.20  4838.0 2094.84  4869.7 2094.69  4874.9 2093.46
  4906.6 2091.51  4918.0 2092.99  4955.0 2094.45  4976.8 2092.37  4994.5 2088.45
  4999.9 2090.48  5018.0 2087.19  5023.5 2088.27  5048.0 2087.11  5048.5 2086.61
  5057.8 2087.11  5070.6 2091.77  5076.1 2090.53  5094.2 2094.27  5099.6 2092.69
  5107.3 2094.28  5151.7 2093.41  5205.3 2094.42  5259.7 2097.20  5367.6 2107.52
#Mann=6,-1,0
  4738.2    0.07       0  4782.0    0.16       0  4918.0    0.07       0
  5048.0    0.07       0  5057.8    0.07       0  5151.7    0.16       0
Bank Sta=5048,5057.8
Exp/Cntr=0.3,0.1

Type RM Length L Ch R = 1,2780,203,203,203
BEGIN DESCRIPTION:
Elm 52 2780.33
END DESCRIPTION:
XS GIS Cut Line= 3
      1516816.67      6771987.07      1517150.00      6771893.32
      1517314.79      6771581.90
#Sta/Elev= 30
  4498.0 2104.71  4517.6 2102.50  4546.5 2097.56  4549.7 2098.02  4585.7 2094.57
  4672.9 2092.81  4693.1 2085.31  4693.4 2083.84  4693.9 2083.34  4703.2 2083.84
  4704.0 2085.49  4724.8 2092.26  4756.9 2093.31  4810.8 2092.66  4866.4 2094.24
  4882.8 2092.04  4888.5 2092.60  4895.5 2090.62  4904.8 2090.18  4948.8 2091.26
  4992.8 2090.06  5008.7 2088.18  5020.5 2084.76  5031.2 2084.39  5042.6 2090.25
  5065.2 2096.42  5119.2 2100.63  5124.8 2101.81  5185.2 2105.07  5196.6 2107.01
#Mann=5,-1,0
  4498.0    0.07       0  4549.7    0.16       0  4693.4    0.07       0
  4703.2    0.16       0  4756.9    0.07       0
Bank Sta=4693.4,4703.2
Exp/Cntr=0.3,0.1

Type RM Length L Ch R = 1,2577,290,290,290
BEGIN DESCRIPTION:
Elm 52 2577.19
END DESCRIPTION:
XS GIS Cut Line= 3
      1516818.01      6771994.87      1517304.95      6771927.17
      1517458.56      6771918.06
#Sta/Elev= 30
  4508.3 2105.16  4531.4 2101.62  4556.7 2097.95  4592.8 2093.92  4656.7 2092.30
  4687.0 2092.46  4717.3 2086.00  4727.4 2085.93  4741.1 2089.24  4747.6 2092.19
  4757.4 2092.30  4828.3 2091.25  4870.5 2091.38  4884.4 2091.08  4889.5 2091.84
  4909.1 2091.91  4969.7 2090.67  4989.9 2088.82  4997.4 2087.15  5002.5 2087.15
  5020.0 2083.32  5025.1 2083.06  5025.6 2082.56  5034.9 2083.06  5040.0 2086.30
  5060.1 2092.28  5072.7 2093.90  5100.1 2100.09  5130.2 2103.35  5153.8 2103.15
#Mann=7,-1,0
  4508.3    0.16       0  4531.4    0.07       0  4556.7    0.16       0
  4757.4    0.07       0  4870.5    0.16       0  5025.1    0.07       0
  5034.9    0.16       0
Bank Sta=5025.1,5034.9
Exp/Cntr=0.3,0.1

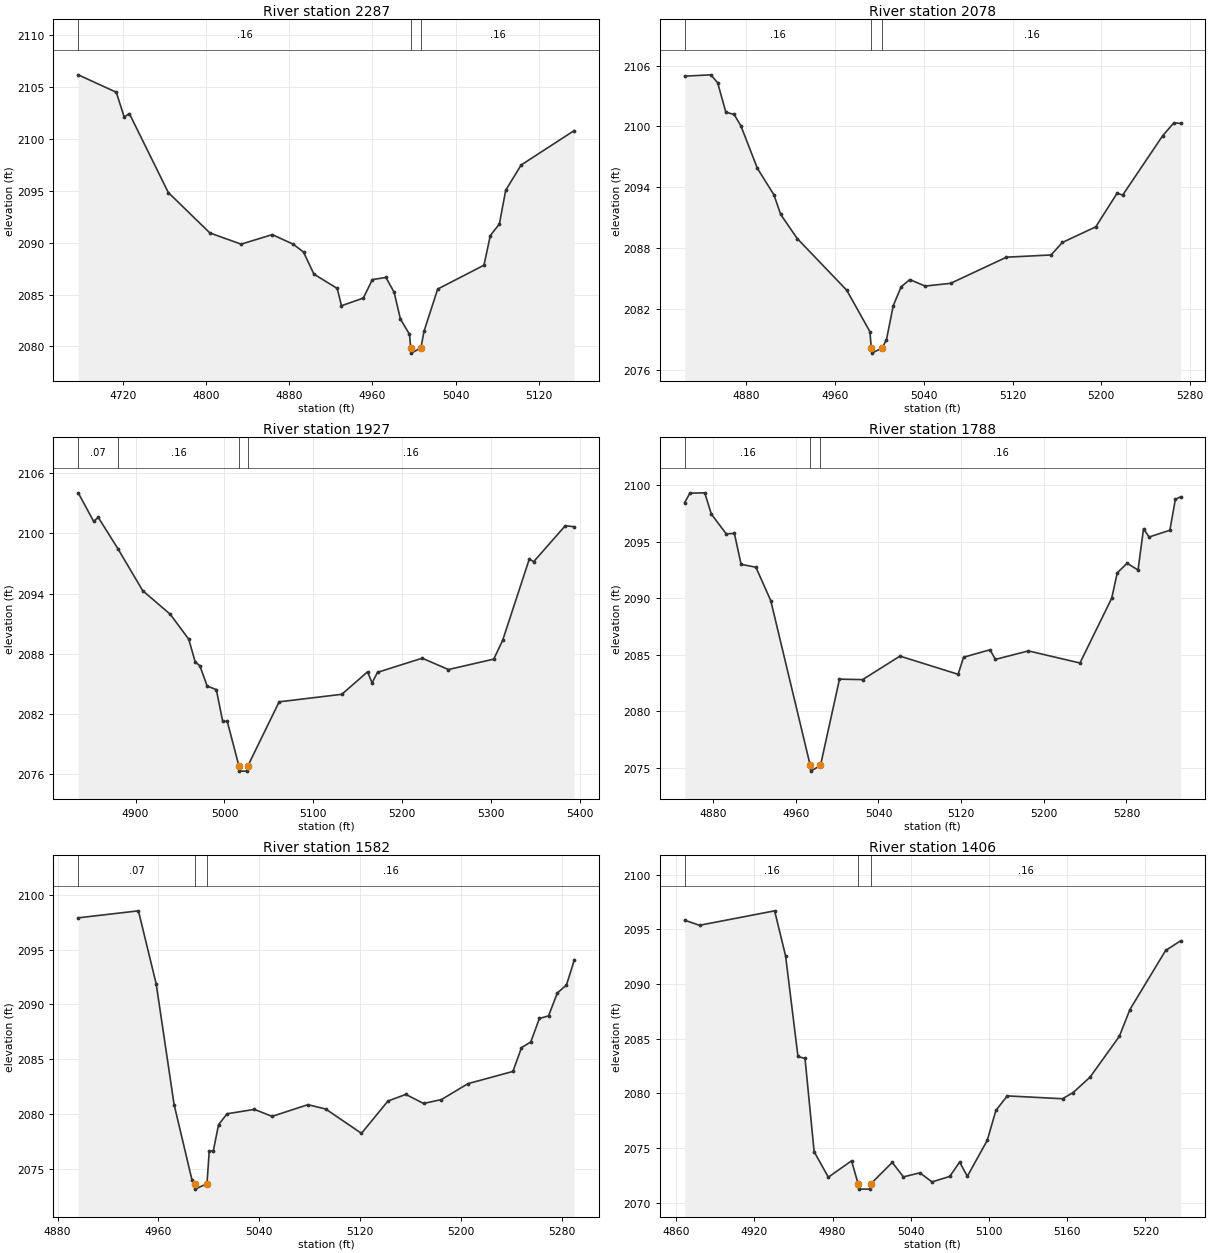
Type RM Length L Ch R = 1,2287,209,209,209
BEGIN DESCRIPTION:
Elm 52 2287.21
END DESCRIPTION:
XS GIS Cut Line= 3
      1516798.45      6772041.75      1517043.23      6772048.26
      1517233.36      6772181.09
#Sta/Elev= 30
  4677.1 2106.20  4713.7 2104.52  4721.3 2102.13  4726.3 2102.46  4763.7 2094.85
  4803.7 2090.95  4833.7 2089.87  4863.7 2090.79  4883.7 2089.87  4893.7 2089.11
  4903.7 2086.98  4926.1 2085.60  4930.2 2083.93  4951.2 2084.67  4959.9 2086.45
  4972.9 2086.66  4980.8 2085.24  4986.9 2082.64  4995.6 2081.18  4996.8 2079.86
  4997.3 2079.36  5006.6 2079.86  5009.5 2081.45  5022.7 2085.54  5067.2 2087.84
  5073.3 2090.70  5082.0 2091.81  5088.1 2095.07  5102.9 2097.50  5153.9 2100.82
#Mann=3,-1,0
  4677.1    0.16       0  4996.8    0.07       0  5006.6    0.16       0
Bank Sta=4996.8,5006.6
Exp/Cntr=0.3,0.1

Type RM Length L Ch R = 1,2078,151,151,151
BEGIN DESCRIPTION:
Elm 52 2077.96
END DESCRIPTION:
XS GIS Cut Line= 3
      1516794.51      6772106.84      1516975.52      6772231.86
      1517200.99      6772207.24
#Sta/Elev= 30
  4824.6 2104.96  4848.2 2105.09  4854.3 2104.31  4861.7 2101.40  4869.2 2101.18
  4875.3 2100.04  4890.1 2095.86  4905.0 2093.25  4911.1 2091.31  4926.0 2088.93
  4970.6 2083.83  4991.5 2079.74  4992.7 2078.12  4993.2 2077.62  5002.5 2078.12
  5006.4 2078.95  5012.5 2082.30  5019.6 2084.17  5027.4 2084.88  5041.2 2084.24
  5064.2 2084.51  5114.5 2087.09  5154.7 2087.31  5164.8 2088.54  5195.0 2090.09
  5214.2 2093.41  5219.2 2093.22  5255.3 2099.09  5265.4 2100.36  5271.4 2100.29
#Mann=3,-1,0
  4824.6    0.16       0  4992.7    0.07       0  5002.5    0.16       0
Bank Sta=4992.7,5002.5
Exp/Cntr=0.3,0.1

Type RM Length L Ch R = 1,1927,139,139,139
BEGIN DESCRIPTION:
Elm 52 1927.23
END DESCRIPTION:
XS GIS Cut Line= 3
      1516654.97      6772237.99      1516813.84      6772281.05
      1517204.97      6772238.00
#Sta/Elev= 30
  4835.4 2104.04  4852.8 2101.19  4857.9 2101.60  4880.0 2098.48  4908.0 2094.28
  4939.0 2091.93  4959.8 2089.44  4967.1 2087.16  4972.3 2086.80  4980.5 2084.77
  4990.8 2084.42  4998.0 2081.26  5003.1 2081.26  5016.3 2076.79  5016.8 2076.29
  5025.7 2076.29  5026.2 2076.79  5061.5 2083.20  5132.0 2083.95  5161.0 2086.19
  5166.1 2085.09  5172.2 2086.14  5222.5 2087.55  5252.0 2086.42  5303.0 2087.46
  5313.0 2089.32  5343.0 2097.43  5348.0 2097.18  5383.5 2100.76  5393.5 2100.66
#Mann=4,-1,0
  4835.4    0.07       0  4880.0    0.16       0  5016.3    0.07       0
  5026.2    0.16       0
Bank Sta=5016.3,5026.2
Exp/Cntr=0.3,0.1

Type RM Length L Ch R = 1,1788,206,206,206
BEGIN DESCRIPTION:
Elm 52 1788.45
END DESCRIPTION:
XS GIS Cut Line= 3
      1516786.73      6772476.64      1516903.91      6772381.60
      1517213.76      6772270.93
#Sta/Elev= 30
  4852.5 2098.46  4857.5 2099.30  4871.9 2099.33  4878.3 2097.45  4892.7 2095.70
  4900.6 2095.74  4907.1 2093.00  4921.4 2092.75  4935.8 2089.79  4974.0 2075.20
  4974.5 2074.70  4983.9 2075.20  5002.3 2082.84  5024.7 2082.80  5060.8 2084.88
  5117.1 2083.27  5122.4 2084.78  5147.9 2085.44  5153.2 2084.59  5185.1 2085.34
  5235.0 2084.27  5265.7 2090.00  5271.1 2092.25  5280.6 2093.10  5291.2 2092.50
  5296.5 2096.15  5301.9 2095.42  5322.0 2096.02  5327.3 2098.75  5332.4 2098.98
#Mann=3,-1,0
  4852.5    0.16       0  4974.0    0.07       0  4983.9    0.16       0
Bank Sta=4974,4983.9
Exp/Cntr=0.3,0.1

Type RM Length L Ch R = 1,1582,176,176,176
BEGIN DESCRIPTION:
Elm 52 1581.66
END DESCRIPTION:
XS GIS Cut Line= 3
      1516992.48      6772572.97      1517065.37      6772498.78
      1517277.77      6772301.92
#Sta/Elev= 30
  4896.3 2097.92  4944.1 2098.56  4958.2 2091.87  4972.4 2080.85  4986.5 2074.00
  4988.6 2073.62  4989.1 2073.12  4998.5 2073.62  5000.3 2076.61  5003.5 2076.61
  5007.7 2079.02  5014.5 2080.01  5036.1 2080.41  5050.2 2079.77  5078.6 2080.84
  5092.8 2080.44  5121.1 2078.22  5142.1 2081.17  5156.3 2081.78  5170.4 2080.95
  5184.6 2081.31  5205.6 2082.76  5241.3 2083.88  5248.1 2086.05  5255.5 2086.58
  5262.3 2088.72  5269.6 2088.96  5276.5 2091.04  5283.8 2091.78  5289.9 2094.02
#Mann=3,-1,0
  4896.3    0.07       0  4988.6    0.07       0  4998.5    0.16       0
Bank Sta=4988.6,4998.5
Exp/Cntr=0.3,0.1

Type RM Length L Ch R = 1,1406,200,200,200
BEGIN DESCRIPTION:
Elm 52 1405.65
END DESCRIPTION:
XS GIS Cut Line= 3
      1517173.46      6772658.90      1517225.52      6772540.45
      1517359.61      6772328.25
#Sta/Elev= 30
  4866.6 2095.83  4878.0 2095.37  4935.6 2096.69  4944.0 2092.57  4953.5 2083.38
  4958.9 2083.20  4965.9 2074.68  4976.8 2072.35  4994.6 2073.85  4999.6 2071.76
  5000.1 2071.26  5009.0 2071.26  5009.5 2071.76  5025.8 2073.70  5034.4 2072.38
  5047.0 2072.75  5056.3 2071.92  5069.9 2072.42  5077.5 2073.73  5083.4 2072.43
  5098.7 2075.72  5105.3 2078.45  5114.0 2079.78  5156.4 2079.52  5164.5 2080.08
  5177.5 2081.49  5200.0 2085.22  5208.1 2087.67  5235.5 2093.07  5247.0 2093.95
#Mann=3,-1,0
  4866.6    0.16       0  4999.6    0.07       0  5009.5    0.16       0
Bank Sta=4999.6,5009.5
Exp/Cntr=0.3,0.1

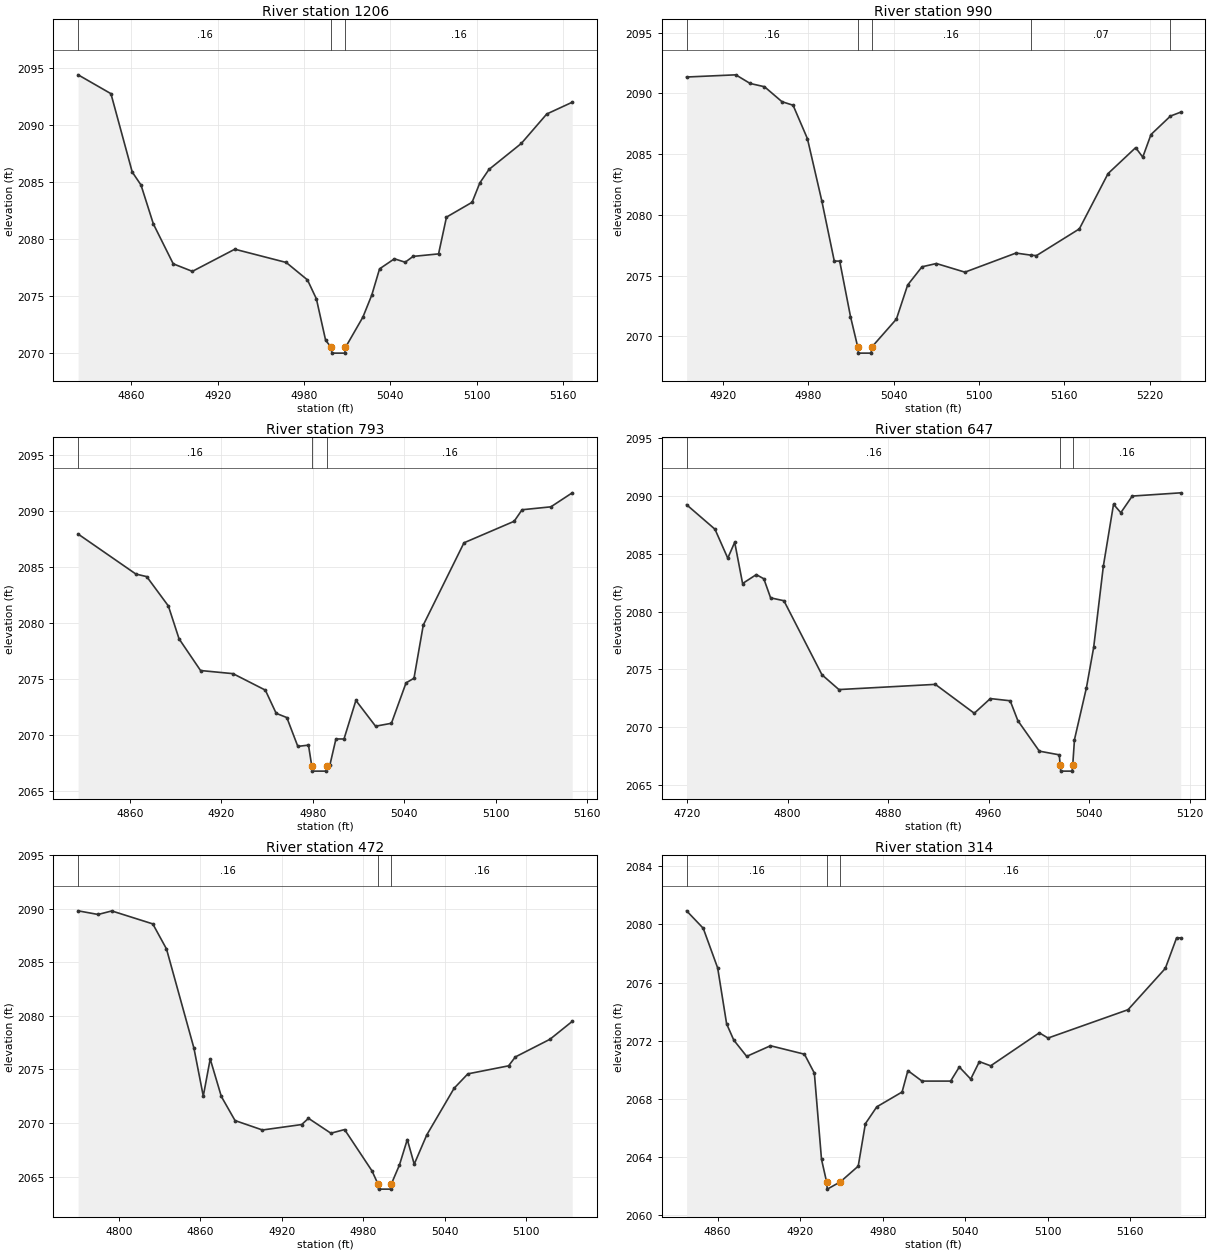
Type RM Length L Ch R = 1,1206,216,216,216
BEGIN DESCRIPTION:
Elm 52 1206.06
END DESCRIPTION:
XS GIS Cut Line= 3
      1517297.13      6772671.97      1517397.40      6772530.03
      1517466.41      6772375.09
#Sta/Elev= 30
  4823.0 2094.39  4845.8 2092.74  4860.6 2085.88  4866.7 2084.74  4875.3 2081.33
  4889.1 2077.84  4902.4 2077.18  4931.9 2079.12  4967.6 2077.96  4982.4 2076.43
  4988.6 2074.77  4995.0 2071.15  4998.9 2070.52  4999.4 2070.02  5008.3 2070.02
  5008.8 2070.52  5020.9 2073.17  5027.1 2075.11  5032.5 2077.40  5042.8 2078.28
  5050.3 2077.98  5055.8 2078.49  5073.5 2078.71  5079.0 2081.93  5096.8 2083.23
  5102.2 2084.93  5108.5 2086.10  5131.0 2088.38  5148.7 2090.96  5166.4 2091.99
#Mann=3,-1,0
  4823.0    0.16       0  4998.9    0.07       0  5008.8    0.16       0
Bank Sta=4998.9,5008.8
Exp/Cntr=0.3,0.1

Type RM Length L Ch R = 1,990,197,197,197
BEGIN DESCRIPTION:
Elm 52 989.61
END DESCRIPTION:
XS GIS Cut Line= 3
      1517561.46      6772742.27      1517575.78      6772635.50
      1517603.13      6772397.19
#Sta/Elev= 30
  4894.3 2091.34  4928.9 2091.52  4939.0 2090.81  4949.1 2090.54  4961.4 2089.31
  4969.2 2089.02  4979.3 2086.27  4989.4 2081.16  4998.2 2076.20  5002.0 2076.20
  5009.6 2071.64  5014.7 2069.13  5015.2 2068.63  5024.1 2068.63  5024.6 2069.13
  5041.9 2071.43  5049.8 2074.23  5059.9 2075.73  5070.0 2076.00  5090.1 2075.29
  5126.0 2076.86  5136.4 2076.69  5140.4 2076.65  5170.6 2078.85  5190.8 2083.40
  5210.2 2085.53  5215.2 2084.75  5221.0 2086.61  5234.7 2088.13  5241.9 2088.45
#Mann=5,-1,0
  4894.3    0.16       0  5014.7    0.07       0  5024.6    0.16       0
  5136.4    0.07       0  5234.7    0.16       0
Bank Sta=5014.7,5024.6
Exp/Cntr=0.3,0.1

Type RM Length L Ch R = 1,793,146,146,146
BEGIN DESCRIPTION:
Elm 52 792.76
END DESCRIPTION:
XS GIS Cut Line= 3
      1517636.97      6772713.64      1517755.47      6772592.53
      1517800.50      6772444.57
#Sta/Elev= 30
  4826.1 2087.95  4864.0 2084.38  4871.1 2084.15  4885.3 2081.53  4892.3 2078.60
  4906.4 2075.77  4927.7 2075.49  4948.9 2074.02  4956.0 2071.95  4963.0 2071.57
  4970.2 2069.00  4977.2 2069.11  4979.3 2067.29  4979.8 2066.79  4988.8 2066.79
  4989.3 2067.29  4991.3 2067.37  4995.2 2069.66  5000.5 2069.66  5008.3 2073.10
  5021.2 2070.80  5031.6 2071.06  5041.2 2074.67  5046.4 2075.08  5052.5 2079.83
  5079.2 2087.17  5112.1 2089.09  5117.3 2090.12  5136.2 2090.38  5150.2 2091.63
#Mann=3,-1,0
  4826.1    0.16       0  4979.3    0.07       0  4989.3    0.16       0
Bank Sta=4979.3,4989.3
Exp/Cntr=0.3,0.1

Type RM Length L Ch R = 1,647,175,175,175
BEGIN DESCRIPTION:
Elm 52 646.64
END DESCRIPTION:
XS GIS Cut Line= 3
      1517634.34      6772738.38      1517892.19      6772622.48
      1517988.55      6772567.79
#Sta/Elev= 30
  4719.5 2089.25  4742.1 2087.13  4752.3 2084.62  4757.8 2086.00  4764.1 2082.43
  4775.0 2083.20  4781.0 2082.84  4786.4 2081.19  4797.0 2080.94  4827.3 2074.53
  4840.8 2073.25  4917.6 2073.70  4948.6 2071.20  4961.4 2072.47  4977.2 2072.28
  4983.3 2070.56  5000.4 2067.92  5016.3 2067.60  5017.0 2066.69  5017.5 2066.19
  5026.5 2066.19  5027.0 2066.69  5028.4 2068.92  5037.9 2073.40  5043.7 2076.91
  5051.4 2083.94  5059.5 2089.29  5065.3 2088.56  5074.4 2090.00  5113.0 2090.28
#Mann=3,-1,0
  4719.5    0.16       0  5017.0    0.07       0  5027.0    0.16       0
Bank Sta=5017,5027
Exp/Cntr=0.3,0.1

Type RM Length L Ch R = 1,472,158,158,158
BEGIN DESCRIPTION:
Elm 52 471.551
END DESCRIPTION:
XS GIS Cut Line= 3
      1517600.48      6772795.67      1517828.39      6772764.71
      1517961.30      6772747.64
#Sta/Elev= 30
  4770.0 2089.81  4784.7 2089.47  4794.8 2089.80  4825.0 2088.59  4835.1 2086.25
  4855.3 2077.00  4862.2 2072.51  4867.3 2075.98  4875.5 2072.48  4885.6 2070.23
  4905.8 2069.35  4934.7 2069.86  4939.7 2070.44  4956.2 2069.05  4966.3 2069.39
  4986.5 2065.53  4990.8 2064.33  4991.3 2063.83  5000.3 2063.83  5000.8 2064.33
  5006.7 2066.08  5012.5 2068.46  5017.6 2066.16  5026.8 2068.88  5047.0 2073.25
  5057.1 2074.59  5087.1 2075.34  5092.1 2076.17  5117.6 2077.82  5134.0 2079.49
#Mann=3,-1,0
  4770.0    0.16       0  4990.8    0.07       0  5000.8    0.16       0
Bank Sta=4990.8,5000.8
Exp/Cntr=0.3,0.1

Type RM Length L Ch R = 1,314,136,136,136
BEGIN DESCRIPTION:
Elm 52 4965
END DESCRIPTION:
XS GIS Cut Line= 3
      1517643.48      6772932.38      1517798.07      6772881.97
      1517954.71      6772762.99
#Sta/Elev= 30
  4837.4 2080.94  4849.5 2079.74  4860.0 2077.01  4866.5 2073.17  4871.7 2072.05
  4881.1 2070.93  4898.4 2071.66  4923.1 2071.08  4930.3 2069.78  4935.5 2063.85
  4939.2 2062.30  4939.7 2061.80  4949.2 2062.30  4962.2 2063.38  4967.4 2066.30
  4975.7 2067.46  4994.1 2068.48  4998.3 2069.95  5008.6 2069.23  5029.4 2069.23
  5035.7 2070.20  5044.0 2069.37  5050.3 2070.57  5058.5 2070.28  5093.9 2072.55
  5100.2 2072.19  5158.4 2074.14  5185.5 2076.98  5193.7 2079.08  5196.7 2079.08
#Mann=3,-1,0
  4837.4    0.16       0  4939.2    0.07       0  4949.2    0.16       0
Bank Sta=4939.2,4949.2
Exp/Cntr=0.3,0.1

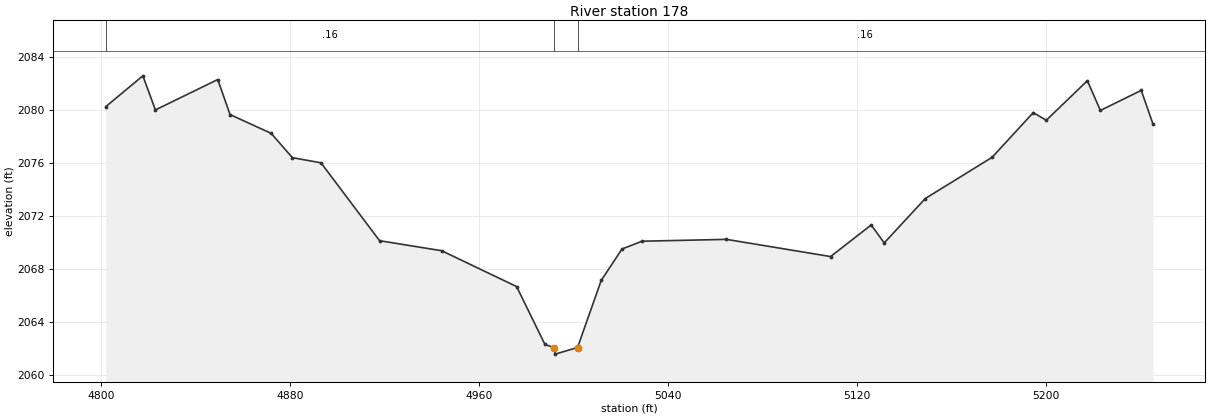
Type RM Length L Ch R = 1,178,0,0,0
BEGIN DESCRIPTION:
Elm 52 4964
END DESCRIPTION:
XS GIS Cut Line= 3
      1517708.60      6773039.15      1517896.54      6772976.52
      1518000.13      6772754.27
#Sta/Elev= 30
  4801.9 2080.28  4817.6 2082.61  4822.9 2080.03  4849.3 2082.33  4854.5 2079.68
  4871.9 2078.26  4880.9 2076.42  4893.0 2076.03  4917.8 2070.14  4944.1 2069.38
  4975.8 2066.67  4987.8 2062.29  4991.6 2062.06  4992.1 2061.56  5001.6 2062.06
  5011.6 2067.13  5020.4 2069.51  5028.9 2070.10  5064.6 2070.24  5108.7 2068.94
  5125.9 2071.33  5131.4 2069.97  5148.8 2073.33  5177.1 2076.45  5194.5 2079.83
  5200.0 2079.25  5217.4 2082.24  5222.9 2079.99  5240.2 2081.51  5245.2 2078.95
#Mann=3,-1,0
  4801.9    0.16       0  4991.6    0.07       0  5001.6    0.16       0
Bank Sta=4991.6,5001.6
Exp/Cntr=0.3,0.1

Chan Stop Cuts=-1