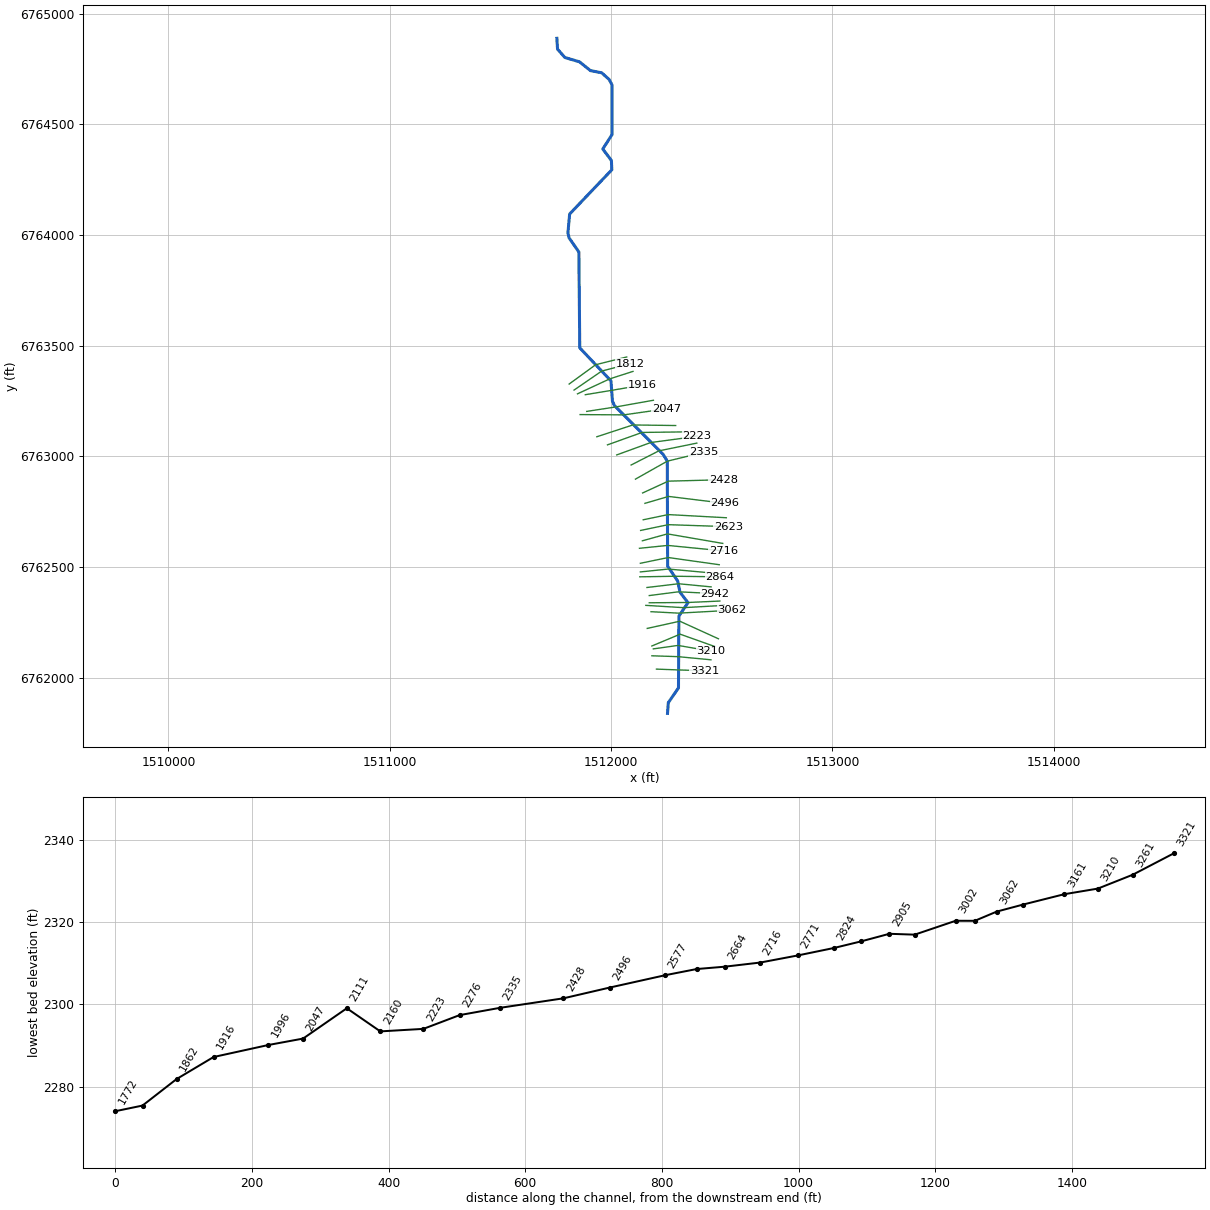
--- Elm 53.prj (project) ---

Proj Title=Elm 53 Base Level Engineering
Current Plan=p01
Default Exp/Contr=0.3,0.1
English Units
Geom File=g01
Flow File=f01
Plan File=p01
BEGIN DESCRIPTION:
Elm 53
END DESCRIPTION:

--- Elm 53.p01 (plan) ---

Plan Title=Multiple Run
Short Identifier=Multiple
Geom File=g01
Flow File=f01
Subcritical Flow
K Sum by GR= 0
Std Step Tol= 0.01
Critical Tol= 0.01
Num of Std Step Trials= 20
Max Error Tol= 0.3
Flow Tol Ratio= 0.001
Split Flow NTrial= 30
Split Flow Tol= 0.02
Split Flow Ratio= 0.02
Log Output Level= 0
Friction Slope Method= 1
Unsteady Friction Slope Method= 2
Unsteady Bridges Friction Slope Method= 1
Parabolic Critical Depth
Global Vel Dist=  1 , 1 , 1
Global Log Level= 0
CheckData=True
Encroach Param= -1, 0, 0, 0
BEGIN DESCRIPTION:
Multiple Run
END DESCRIPTION:

--- Elm 53.f01 (steady flow) ---

Flow Title=Multiple
Number of Profiles=7
Profile Names=10-year,25-year,50-year,1pct_min,100-year,1pct_plu,500-year
River Rch & RM= Elm 53,Reach-1,3321
     223     314     391     303     486     668     758
Boundary for River Rch & Prof#=Elm 53,Reach-1,1
Up Type=0
Dn Type=3
Dn Slope=0.005
Boundary for River Rch & Prof#=Elm 53,Reach-1,2
Up Type=0
Dn Type=3
Dn Slope=0.005
Boundary for River Rch & Prof#=Elm 53,Reach-1,3
Up Type=0
Dn Type=3
Dn Slope=0.005
Boundary for River Rch & Prof#=Elm 53,Reach-1,4
Up Type=0
Dn Type=3
Dn Slope=0.005
Boundary for River Rch & Prof#=Elm 53,Reach-1,5
Up Type=0
Dn Type=3
Dn Slope=0.005
Boundary for River Rch & Prof#=Elm 53,Reach-1,6
Up Type=0
Dn Type=3
Dn Slope=0.005
Boundary for River Rch & Prof#=Elm 53,Reach-1,7
Up Type=0
Dn Type=3
Dn Slope=0.005

--- Elm 53.g01 (geometry) ---

Geom Title=Existing Conditions

River Reach=Elm 53,Reach-1
Reach XY= 30
      1512255.00      6761838.00      1512258.65      6761886.49
      1512304.55      6761953.19      1512306.38      6762277.56
      1512347.47      6762338.01      1512311.39      6762385.71
      1512300.84      6762436.25      1512255.51      6762503.21
      1512253.95      6762977.57      1512235.40      6763008.16
      1512015.52      6763228.21      1512006.17      6763248.48
      1511999.48      6763340.43      1511858.54      6763489.46
      1511854.48      6763922.78      1511810.68      6763985.69
      1511804.90      6764008.10      1511812.76      6764094.17
      1512003.34      6764294.05      1512001.43      6764336.35
      1511962.59      6764387.99      1512004.34      6764453.16
      1512004.02      6764677.72      1511991.78      6764701.67
      1511957.58      6764732.29      1511906.77      6764742.20
      1511857.18      6764781.91      1511791.45      6764801.37
      1511758.14      6764839.03      1511755.00      6764888.00

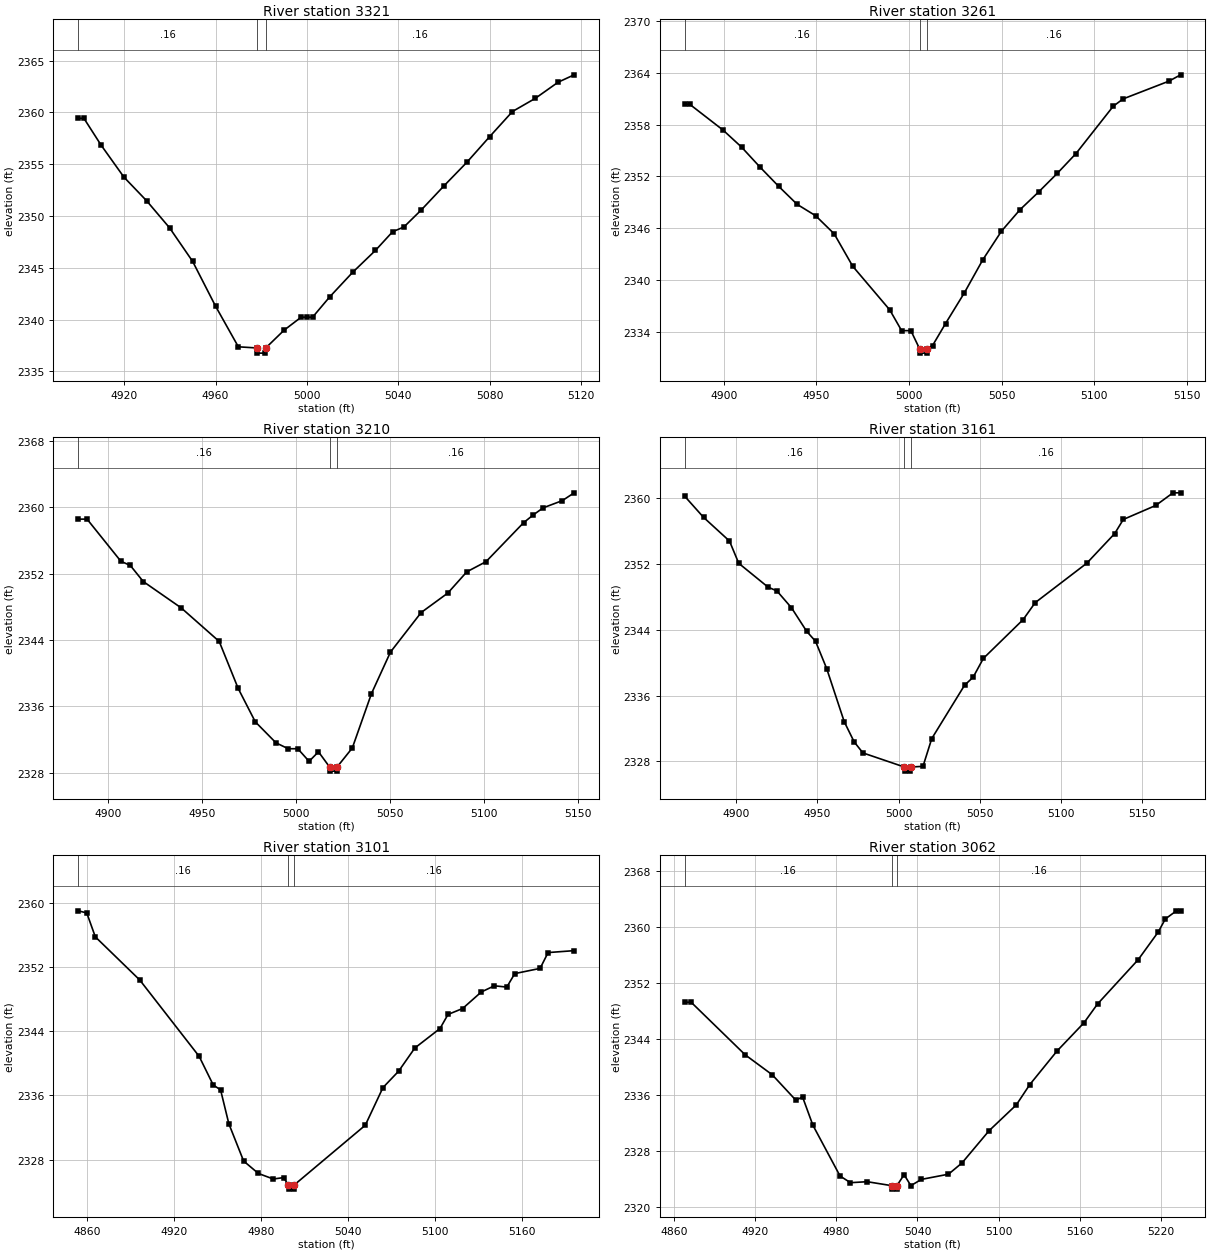
Type RM Length L Ch R = 1,3321,60,60,60
BEGIN DESCRIPTION:
Elm 53 3320.541
END DESCRIPTION:
XS GIS Cut Line= 3
      1512204.98      6762038.00      1512305.01      6762034.28
      1512421.95      6762030.53
#Sta/Elev= 30
  4899.9 2359.42  4902.4 2359.42  4909.9 2356.84  4919.9 2353.75  4929.9 2351.45
  4939.9 2348.85  4950.0 2345.61  4960.0 2341.30  4970.0 2337.37  4978.0 2337.26
  4978.2 2336.76  4981.7 2336.76  4982.0 2337.26  4990.0 2338.97  4997.5 2340.23
  5000.0 2340.23  5002.5 2340.23  5010.0 2342.19  5020.0 2344.55  5030.0 2346.67
  5037.5 2348.47  5042.5 2348.94  5050.0 2350.56  5060.0 2352.90  5070.0 2355.17
  5080.0 2357.65  5090.0 2360.08  5100.0 2361.35  5110.0 2362.91  5117.0 2363.62
#Mann=3,-1,0
  4899.9    0.16       0  4978.0    0.07       0  4982.0    0.16       0
Bank Sta=4978,4982
Exp/Cntr=0.3,0.1

Type RM Length L Ch R = 1,3261,51,51,51
BEGIN DESCRIPTION:
Elm 53 3260.8
END DESCRIPTION:
XS GIS Cut Line= 3
      1512184.32      6762098.18      1512302.78      6762094.27
      1512451.28      6762080.07
#Sta/Elev= 30
  4878.9 2360.33  4881.7 2360.33  4899.6 2357.36  4909.6 2355.39  4919.6 2353.07
  4929.6 2350.86  4939.6 2348.77  4949.6 2347.45  4959.6 2345.36  4969.6 2341.61
  4989.6 2336.56  4996.0 2334.16  5001.0 2334.16  5005.7 2332.06  5006.0 2331.56
  5009.5 2331.56  5009.7 2332.06  5012.7 2332.44  5019.7 2334.98  5029.8 2338.51
  5039.8 2342.35  5049.9 2345.67  5059.9 2348.15  5070.0 2350.21  5080.0 2352.35
  5090.1 2354.64  5110.2 2360.11  5115.5 2360.96  5140.3 2363.02  5146.6 2363.75
#Mann=3,-1,0
  4878.9    0.16       0  5005.7    0.07       0  5009.7    0.16       0
Bank Sta=5005.7,5009.7
Exp/Cntr=0.3,0.1

Type RM Length L Ch R = 1,3210,49,49,49
BEGIN DESCRIPTION:
Elm 53 3210.27
END DESCRIPTION:
XS GIS Cut Line= 3
      1512190.76      6762129.42      1512302.78      6762145.05
      1512451.25      6762119.23
#Sta/Elev= 30
  4884.0 2358.56  4888.7 2358.56  4906.7 2353.48  4911.7 2352.98  4918.6 2351.04
  4938.8 2347.86  4959.0 2343.82  4969.1 2338.15  4978.2 2334.13  4989.2 2331.60
  4995.7 2330.89  5000.8 2330.89  5006.8 2329.37  5011.8 2330.52  5017.7 2328.69
  5017.9 2328.19  5021.4 2328.19  5021.7 2328.69  5029.8 2330.98  5040.0 2337.54
  5050.1 2342.54  5066.4 2347.30  5080.6 2349.65  5090.7 2352.21  5100.9 2353.43
  5120.9 2358.13  5126.0 2359.06  5131.3 2359.92  5141.5 2360.79  5147.8 2361.73
#Mann=3,-1,0
  4884.0    0.16       0  5017.7    0.07       0  5021.7    0.16       0
Bank Sta=5017.7,5021.7
Exp/Cntr=0.3,0.1

Type RM Length L Ch R = 1,3161,60,60,60
BEGIN DESCRIPTION:
Elm 53 3161.49
END DESCRIPTION:
XS GIS Cut Line= 3
      1512184.32      6762142.46      1512311.89      6762195.83
      1512469.45      6762139.84
#Sta/Elev= 30
  4868.2 2360.19  4879.8 2357.63  4895.8 2354.75  4901.5 2352.05  4919.6 2349.15
  4925.0 2348.70  4934.0 2346.65  4943.4 2343.78  4948.8 2342.59  4955.7 2339.26
  4966.5 2332.82  4972.6 2330.38  4978.0 2329.04  5003.5 2327.33  5003.7 2326.83
  5007.2 2326.83  5007.5 2327.33  5015.0 2327.41  5020.4 2330.78  5040.6 2337.25
  5045.9 2338.23  5052.2 2340.51  5076.7 2345.22  5084.1 2347.27  5115.9 2352.06
  5133.1 2355.66  5138.4 2357.37  5158.4 2359.07  5169.0 2360.60  5173.7 2360.60
#Mann=3,-1,0
  4868.2    0.16       0  5003.5    0.07       0  5007.5    0.16       0
Bank Sta=5003.5,5007.5
Exp/Cntr=0.3,0.1

Type RM Length L Ch R = 1,3101,39,39,39
BEGIN DESCRIPTION:
Elm 53 3101.36
END DESCRIPTION:
XS GIS Cut Line= 3
      1512163.50      6762221.88      1512310.59      6762254.43
      1512485.11      6762174.98
#Sta/Elev= 30
  4853.8 2358.99  4859.7 2358.73  4865.6 2355.75  4896.3 2350.37  4937.3 2340.86
  4947.0 2337.30  4952.1 2336.68  4957.8 2332.46  4968.0 2327.82  4978.2 2326.27
  4988.5 2325.58  4995.7 2325.76  4998.8 2324.82  4999.1 2324.32  5002.6 2324.32
  5002.8 2324.82  5052.0 2332.28  5064.2 2336.97  5075.0 2339.01  5086.2 2341.90
  5103.6 2344.33  5109.1 2346.08  5119.2 2346.82  5132.1 2348.88  5141.1 2349.65
  5149.7 2349.49  5155.2 2351.17  5172.7 2351.82  5178.2 2353.79  5196.2 2354.03
#Mann=3,-1,0
  4853.8    0.16       0  4998.8    0.07       0  5002.8    0.16       0
Bank Sta=4998.8,5002.8
Exp/Cntr=0.3,0.1

Type RM Length L Ch R = 1,3062,32,32,32
BEGIN DESCRIPTION:
Elm 53 3062.38
END DESCRIPTION:
XS GIS Cut Line= 3
      1512180.39      6762297.40      1512305.38      6762290.89
      1512546.27      6762303.91
#Sta/Elev= 30
  4868.0 2349.26  4872.8 2349.26  4912.7 2341.76  4932.7 2338.91  4950.1 2335.29
  4955.1 2335.74  4962.7 2331.72  4982.8 2324.46  4990.5 2323.51  5002.8 2323.65
  5020.8 2323.09  5021.1 2322.59  5024.6 2322.59  5024.8 2323.09  5030.1 2324.65
  5035.1 2323.09  5042.9 2323.98  5062.9 2324.72  5072.9 2326.33  5092.9 2330.93
  5113.0 2334.61  5123.0 2337.52  5143.0 2342.28  5163.0 2346.33  5173.0 2349.01
  5203.1 2355.35  5217.9 2359.30  5223.1 2361.15  5231.3 2362.31  5234.4 2362.31
#Mann=3,-1,0
  4868.0    0.16       0  5020.8    0.07       0  5024.8    0.16       0
Bank Sta=5020.8,5024.8
Exp/Cntr=0.3,0.1

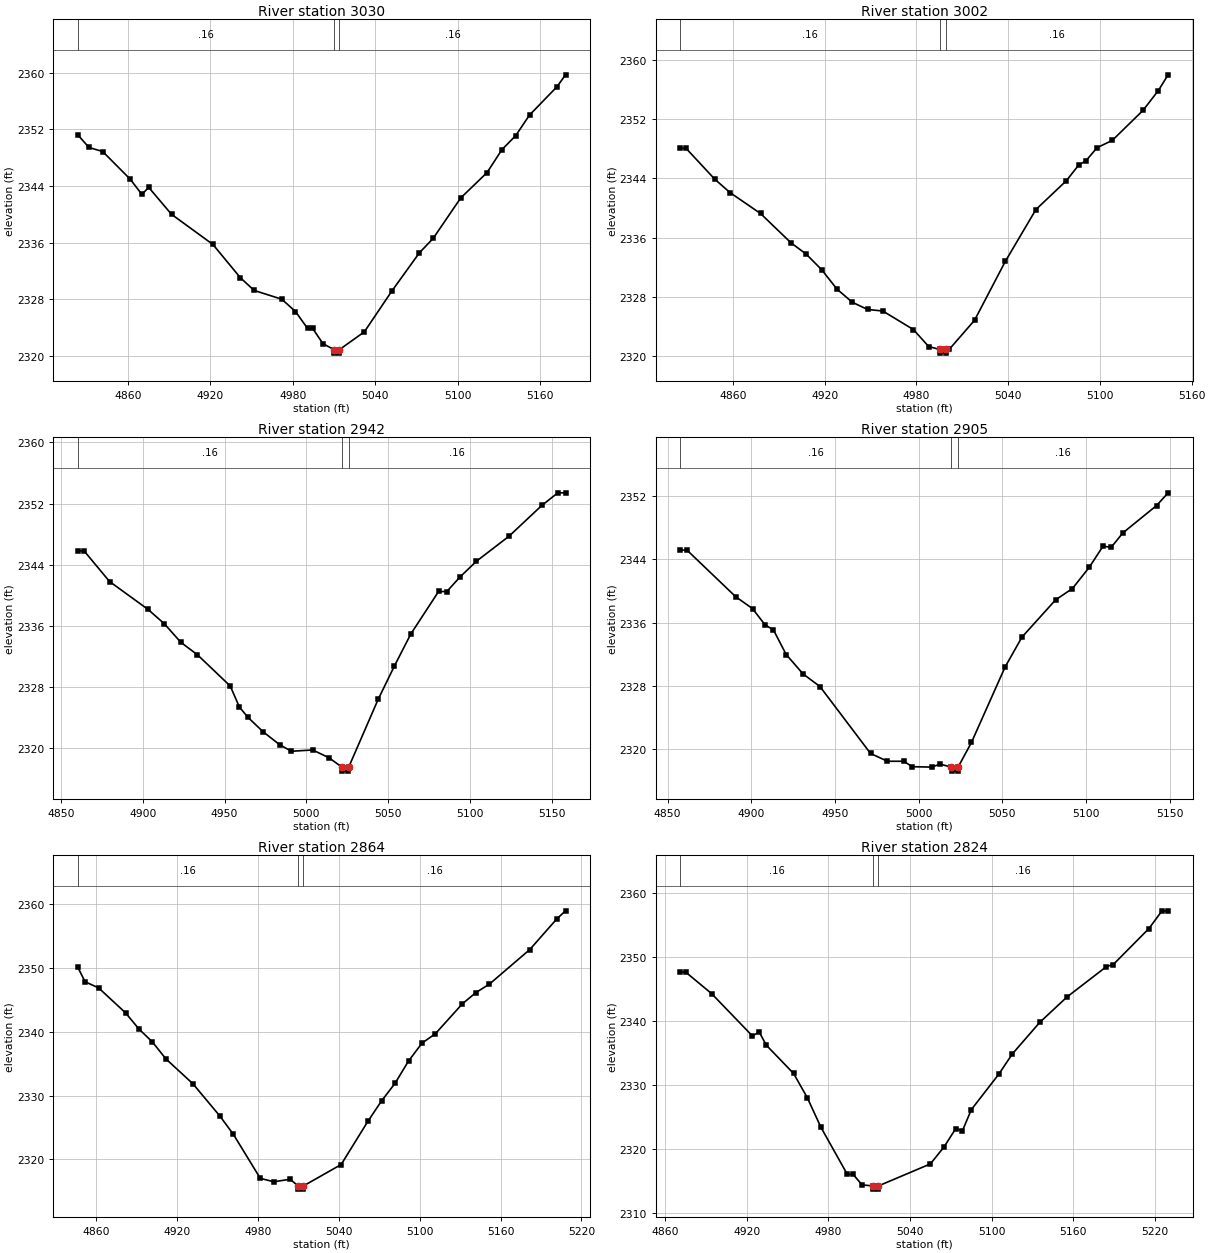
Type RM Length L Ch R = 1,3030,28,28,28
BEGIN DESCRIPTION:
Elm 53 3029.9
END DESCRIPTION:
XS GIS Cut Line= 3
      1512156.90      6762326.04      1512327.52      6762315.62
      1512511.19      6762325.97
#Sta/Elev= 30
  4823.5 2351.24  4831.6 2349.45  4841.6 2348.88  4861.7 2344.95  4870.1 2342.81
  4875.1 2343.80  4891.7 2339.99  4921.8 2335.73  4941.8 2331.02  4951.8 2329.22
  4971.9 2327.98  4981.9 2326.24  4990.7 2323.84  4994.4 2323.84  5001.9 2321.69
  5009.9 2320.85  5010.2 2320.35  5013.7 2320.35  5013.9 2320.85  5032.0 2323.36
  5052.0 2329.13  5072.0 2334.53  5082.1 2336.59  5102.1 2342.30  5121.3 2345.90
  5132.1 2349.14  5142.2 2351.14  5152.2 2354.04  5172.2 2358.05  5178.4 2359.73
#Mann=3,-1,0
  4823.5    0.16       0  5009.9    0.07       0  5013.9    0.16       0
Bank Sta=5009.9,5013.9
Exp/Cntr=0.3,0.1

Type RM Length L Ch R = 1,3002,60,60,60
BEGIN DESCRIPTION:
Elm 53 3002.13
END DESCRIPTION:
XS GIS Cut Line= 3
      1512172.57      6762337.76      1512348.35      6762339.06
      1512491.42      6762345.51
#Sta/Elev= 30
  4825.6 2348.08  4829.3 2348.08  4848.0 2343.92  4858.0 2342.10  4878.0 2339.26
  4898.0 2335.28  4908.0 2333.74  4918.0 2331.65  4928.0 2329.03  4938.0 2327.25
  4948.0 2326.27  4958.0 2326.06  4978.0 2323.55  4988.0 2321.25  4995.2 2320.86
  4995.5 2320.36  4999.0 2320.36  4999.2 2320.86  5001.4 2320.86  5018.0 2324.81
  5038.1 2332.77  5058.1 2339.79  5078.1 2343.71  5086.0 2345.79  5091.0 2346.43
  5098.1 2348.16  5108.1 2349.16  5128.2 2353.22  5138.2 2355.90  5144.6 2358.03
#Mann=3,-1,0
  4825.6    0.16       0  4995.2    0.07       0  4999.2    0.16       0
Bank Sta=4995.2,4999.2
Exp/Cntr=0.3,0.1

Type RM Length L Ch R = 1,2942,37,37,37
BEGIN DESCRIPTION:
Elm 53 2941.87
END DESCRIPTION:
XS GIS Cut Line= 3
      1512172.53      6762370.31      1512304.08      6762387.24
      1512469.46      6762379.43
#Sta/Elev= 30
  4860.3 2345.82  4864.1 2345.82  4879.7 2341.80  4903.1 2338.17  4913.2 2336.27
  4923.3 2333.84  4933.4 2332.22  4953.5 2328.12  4959.1 2325.37  4964.2 2324.05
  4973.7 2322.11  4983.8 2320.43  4990.9 2319.58  5003.9 2319.75  5013.9 2318.73
  5021.9 2317.48  5022.1 2316.98  5025.6 2316.98  5025.9 2317.48  5043.9 2326.36
  5053.9 2330.75  5063.9 2334.93  5080.9 2340.50  5085.9 2340.48  5094.0 2342.40
  5104.0 2344.45  5124.0 2347.74  5144.0 2351.76  5153.8 2353.41  5158.5 2353.41
#Mann=3,-1,0
  4860.3    0.16       0  5021.9    0.07       0  5025.9    0.16       0
Bank Sta=5021.9,5025.9
Exp/Cntr=0.3,0.1

Type RM Length L Ch R = 1,2905,41,41,41
BEGIN DESCRIPTION:
Elm 53 2904.51
END DESCRIPTION:
XS GIS Cut Line= 3
      1512162.19      6762406.78      1512305.38      6762423.70
      1512451.91      6762409.56
#Sta/Elev= 30
  4857.7 2345.19  4861.6 2345.19  4890.7 2339.29  4900.8 2337.77  4908.3 2335.71
  4913.3 2335.08  4920.9 2331.96  4931.0 2329.50  4941.1 2327.90  4971.3 2319.43
  4981.4 2318.44  4991.2 2318.44  4996.2 2317.75  5007.8 2317.70  5012.9 2318.08
  5019.6 2317.69  5019.8 2317.19  5023.3 2317.19  5023.6 2317.69  5031.6 2320.82
  5051.7 2330.38  5061.8 2334.17  5081.9 2338.89  5091.9 2340.31  5102.0 2343.01
  5110.1 2345.65  5115.2 2345.57  5122.1 2347.37  5142.2 2350.83  5149.1 2352.44
#Mann=3,-1,0
  4857.7    0.16       0  5019.6    0.07       0  5023.6    0.16       0
Bank Sta=5019.6,5023.6
Exp/Cntr=0.3,0.1

Type RM Length L Ch R = 1,2864,40,40,40
BEGIN DESCRIPTION:
Elm 53 2863.91
END DESCRIPTION:
XS GIS Cut Line= 3
      1512129.61      6762454.95      1512287.15      6762457.55
      1512491.47      6762454.97
#Sta/Elev= 30
  4846.3 2350.10  4851.7 2347.83  4861.7 2346.88  4881.7 2342.97  4891.7 2340.43
  4901.7 2338.39  4911.7 2335.75  4931.7 2331.86  4951.7 2326.81  4961.7 2323.95
  4981.7 2317.05  4991.7 2316.51  5003.9 2316.91  5009.7 2315.86  5010.0 2315.36
  5013.5 2315.36  5013.7 2315.86  5041.7 2319.21  5061.7 2326.03  5071.7 2329.18
  5081.7 2331.93  5091.7 2335.42  5101.7 2338.22  5111.7 2339.71  5131.7 2344.39
  5141.7 2346.14  5151.7 2347.46  5181.7 2352.88  5201.7 2357.67  5208.2 2358.94
#Mann=3,-1,0
  4846.3    0.16       0  5009.7    0.07       0  5013.7    0.16       0
Bank Sta=5009.7,5013.7
Exp/Cntr=0.3,0.1

Type RM Length L Ch R = 1,2824,53,53,53
BEGIN DESCRIPTION:
Elm 53 2823.69
END DESCRIPTION:
XS GIS Cut Line= 3
      1512132.21      6762477.08      1512258.51      6762490.10
      1512489.00      6762469.27
#Sta/Elev= 30
  4871.3 2347.65  4875.2 2347.65  4894.2 2344.30  4924.2 2337.68  4929.2 2338.30
  4934.4 2336.24  4954.5 2331.81  4964.6 2328.01  4974.6 2323.39  4994.0 2316.03
  4998.3 2316.03  5004.8 2314.40  5012.8 2314.24  5013.1 2313.74  5016.6 2313.74
  5016.8 2314.24  5055.0 2317.68  5065.0 2320.32  5073.6 2323.19  5078.6 2322.88
  5085.1 2326.17  5105.2 2331.68  5115.2 2334.86  5135.3 2339.78  5155.4 2343.77
  5184.4 2348.52  5189.4 2348.84  5215.6 2354.46  5225.2 2357.23  5229.7 2357.23
#Mann=3,-1,0
  4871.3    0.16       0  5012.8    0.07       0  5016.8    0.16       0
Bank Sta=5012.8,5016.8
Exp/Cntr=0.3,0.1

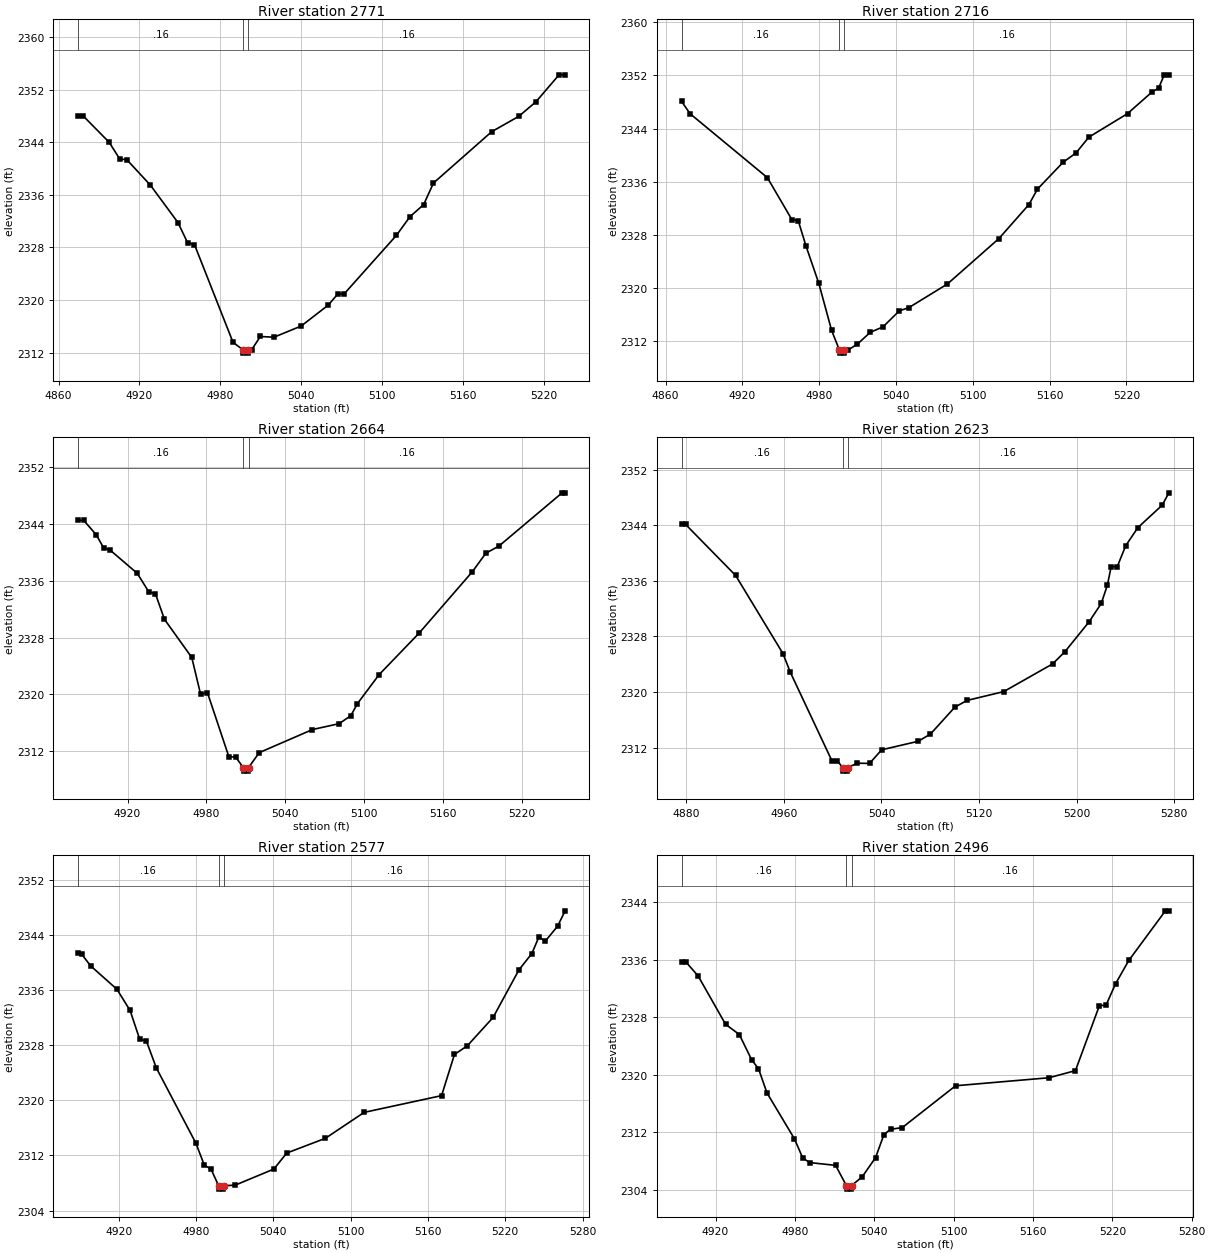
Type RM Length L Ch R = 1,2771,55,55,55
BEGIN DESCRIPTION:
Elm 53 2771.28
END DESCRIPTION:
XS GIS Cut Line= 3
      1512132.17      6762516.14      1512258.51      6762542.19
      1512488.93      6762509.64
#Sta/Elev= 30
  4874.2 2347.99  4878.2 2347.99  4897.5 2343.98  4905.4 2341.42  4910.5 2341.36
  4928.1 2337.46  4948.6 2331.76  4955.7 2328.70  4960.8 2328.43  4989.4 2313.57
  4996.8 2312.42  4997.1 2311.92  5000.6 2311.92  5000.8 2312.42  5003.2 2312.42
  5009.7 2314.45  5019.8 2314.34  5040.0 2316.04  5060.2 2319.24  5067.1 2320.90
  5072.1 2320.97  5110.7 2329.83  5120.8 2332.68  5130.9 2334.50  5138.2 2337.79
  5181.4 2345.59  5201.6 2347.94  5214.3 2350.15  5231.4 2354.24  5235.9 2354.24
#Mann=3,-1,0
  4874.2    0.16       0  4996.8    0.07       0  5000.8    0.16       0
Bank Sta=4996.8,5000.8
Exp/Cntr=0.3,0.1

Type RM Length L Ch R = 1,2716,52,52,52
BEGIN DESCRIPTION:
Elm 53 2716.02
END DESCRIPTION:
XS GIS Cut Line= 3
      1512128.26      6762583.85      1512255.90      6762596.87
      1512507.18      6762572.14
#Sta/Elev= 30
  4872.4 2348.09  4879.2 2346.21  4939.5 2336.60  4958.6 2330.30  4963.6 2330.14
  4969.6 2326.36  4979.7 2320.68  4989.7 2313.61  4995.7 2310.69  4996.0 2310.19
  4999.5 2310.19  4999.7 2310.69  5002.8 2310.69  5009.8 2311.54  5019.9 2313.32
  5029.9 2314.15  5042.6 2316.56  5050.0 2317.03  5080.2 2320.60  5120.4 2327.43
  5143.9 2332.56  5150.5 2334.87  5170.6 2338.92  5180.7 2340.33  5190.7 2342.70
  5220.9 2346.24  5240.2 2349.52  5245.2 2350.07  5249.6 2352.08  5253.2 2352.08
#Mann=3,-1,0
  4872.4    0.16       0  4995.7    0.07       0  4999.7    0.16       0
Bank Sta=4995.7,4999.7
Exp/Cntr=0.3,0.1

Type RM Length L Ch R = 1,2664,41,41,41
BEGIN DESCRIPTION:
Elm 53 2663.94
END DESCRIPTION:
XS GIS Cut Line= 3
      1512141.37      6762617.72      1512254.60      6762648.96
      1512504.57      6762605.99
#Sta/Elev= 30
  4882.1 2344.53  4886.6 2344.53  4896.2 2342.49  4901.7 2340.67  4906.9 2340.31
  4927.4 2337.06  4936.1 2334.47  4941.2 2334.20  4948.1 2330.58  4968.9 2325.20
  4975.6 2320.03  4980.8 2320.26  4997.2 2311.18  5002.3 2311.18  5008.1 2309.68
  5008.4 2309.18  5011.9 2309.18  5012.1 2309.68  5020.3 2311.79  5060.8 2315.04
  5081.1 2315.87  5090.0 2316.99  5095.1 2318.71  5111.6 2322.79  5142.0 2328.63
  5182.6 2337.30  5192.8 2339.89  5202.9 2340.92  5250.9 2348.41  5253.2 2348.41
#Mann=3,-1,0
  4882.1    0.16       0  5008.1    0.07       0  5012.1    0.16       0
Bank Sta=5008.1,5012.1
Exp/Cntr=0.3,0.1

Type RM Length L Ch R = 1,2623,46,46,46
BEGIN DESCRIPTION:
Elm 53 2622.95
END DESCRIPTION:
XS GIS Cut Line= 3
      1512133.50      6762664.58      1512258.51      6762690.62
      1512530.37      6762681.52
#Sta/Elev= 30
  4876.0 2344.14  4879.3 2344.14  4920.4 2336.78  4959.2 2325.54  4965.3 2322.82
  4999.3 2310.12  5003.7 2310.12  5008.2 2309.11  5008.4 2308.61  5011.9 2308.61
  5012.2 2309.11  5020.2 2309.75  5030.2 2309.72  5040.2 2311.68  5070.2 2312.91
  5080.2 2313.95  5100.2 2317.82  5110.2 2318.79  5140.3 2320.06  5180.3 2324.04
  5190.3 2325.77  5210.3 2330.11  5220.3 2332.76  5225.3 2335.40  5228.4 2338.05
  5233.4 2338.05  5240.3 2341.06  5250.3 2343.67  5270.3 2346.91  5275.7 2348.68
#Mann=3,-1,0
  4876.0    0.16       0  5008.2    0.07       0  5012.2    0.16       0
Bank Sta=5008.2,5012.2
Exp/Cntr=0.3,0.1

Type RM Length L Ch R = 1,2577,81,81,81
BEGIN DESCRIPTION:
Elm 53 2577.4
END DESCRIPTION:
XS GIS Cut Line= 3
      1512145.26      6762712.77      1512258.51      6762736.20
      1512520.78      6762721.92
#Sta/Elev= 30
  4888.2 2341.31  4891.2 2341.19  4898.1 2339.50  4918.6 2336.09  4928.8 2333.02
  4936.3 2328.82  4941.4 2328.61  4949.2 2324.68  4979.8 2313.80  4986.5 2310.56
  4991.6 2310.03  4997.5 2307.61  4997.7 2307.11  5001.2 2307.11  5001.5 2307.61
  5010.3 2307.68  5040.4 2310.02  5050.4 2312.34  5080.4 2314.48  5110.5 2318.24
  5170.6 2320.67  5180.6 2326.64  5190.6 2327.90  5210.6 2332.01  5230.7 2338.92
  5240.7 2341.28  5246.1 2343.66  5251.1 2343.07  5260.7 2345.25  5266.5 2347.47
#Mann=3,-1,0
  4888.2    0.16       0  4997.5    0.07       0  5001.5    0.16       0
Bank Sta=4997.5,5001.5
Exp/Cntr=0.3,0.1

Type RM Length L Ch R = 1,2496,68,68,68
BEGIN DESCRIPTION:
Elm 53 2496.15
END DESCRIPTION:
XS GIS Cut Line= 3
      1512153.04      6762786.98      1512259.81      6762818.23
      1512515.05      6762786.98
#Sta/Elev= 30
  4894.3 2335.61  4897.9 2335.61  4906.8 2333.74  4927.6 2327.01  4938.0 2325.59
  4947.3 2322.08  4952.5 2320.84  4958.9 2317.48  4979.7 2311.09  4985.9 2308.45
  4991.1 2307.80  5010.8 2307.41  5018.9 2304.61  5019.1 2304.11  5022.6 2304.11
  5022.9 2304.61  5030.9 2305.82  5041.0 2308.49  5047.3 2311.68  5052.3 2312.42
  5061.2 2312.66  5101.5 2318.47  5172.0 2319.58  5192.1 2320.57  5210.2 2329.60
  5215.2 2329.66  5222.4 2332.63  5232.4 2335.87  5260.1 2342.77  5262.7 2342.77
#Mann=3,-1,0
  4894.3    0.16       0  5018.9    0.07       0  5022.9    0.16       0
Bank Sta=5018.9,5022.9
Exp/Cntr=0.3,0.1

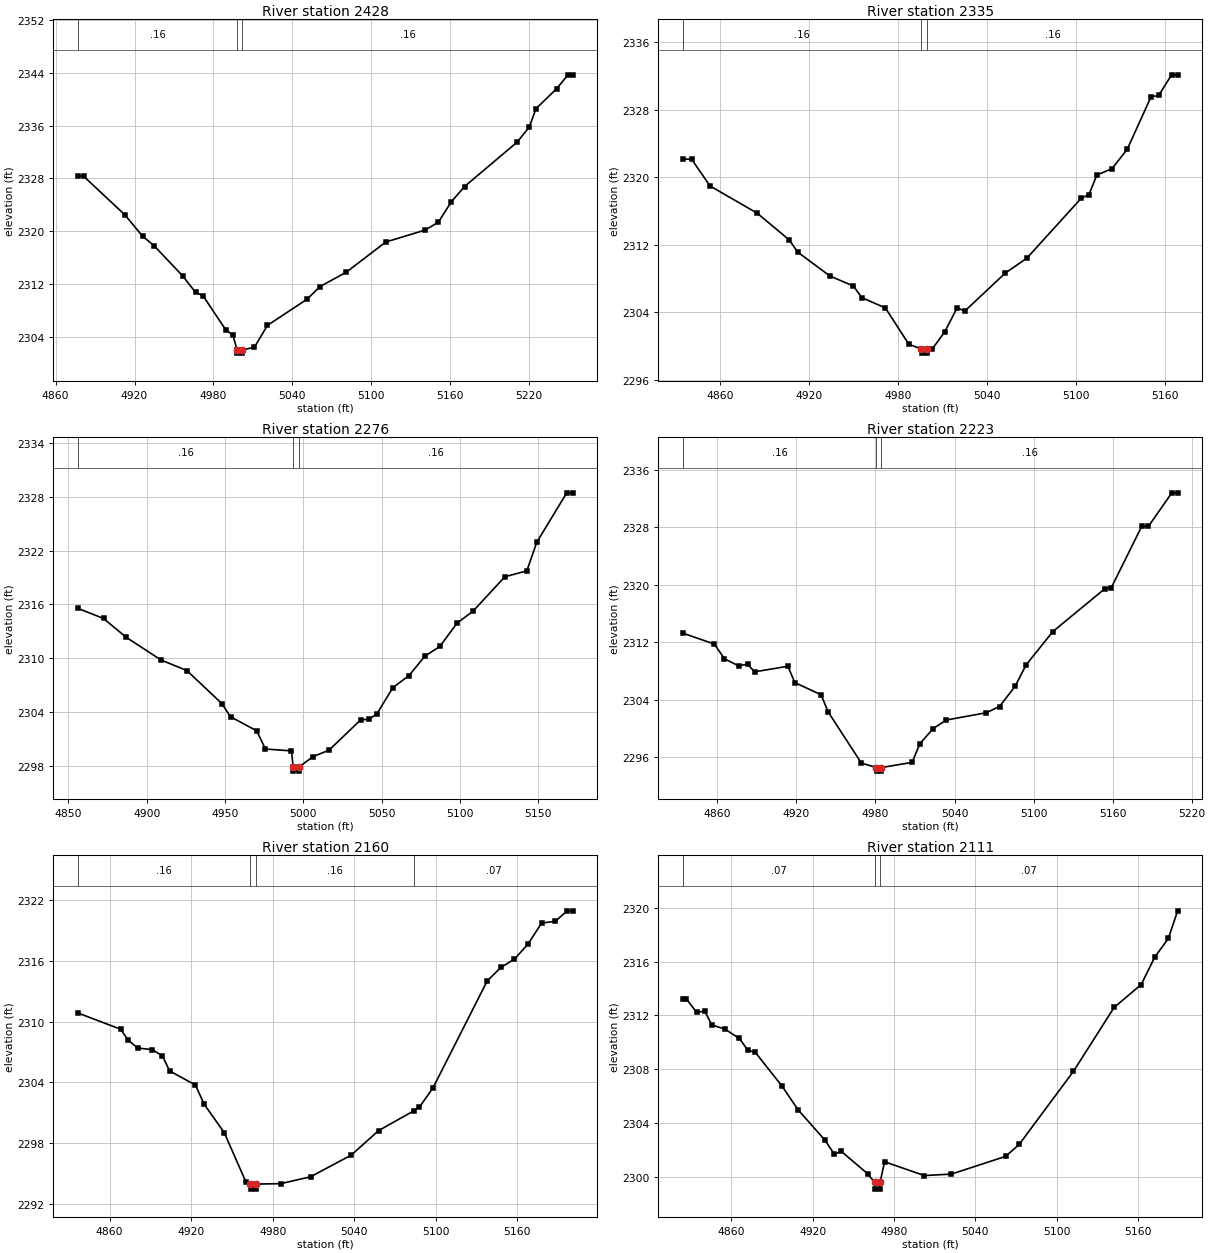
Type RM Length L Ch R = 1,2428,93,93,93
BEGIN DESCRIPTION:
Elm 53 2427.54
END DESCRIPTION:
XS GIS Cut Line= 3
      1512142.63      6762833.86      1512258.51      6762887.24
      1512507.24      6762893.75
#Sta/Elev= 30
  4877.1 2328.35  4881.2 2328.35  4912.7 2322.47  4926.1 2319.24  4934.8 2317.81
  4956.8 2313.17  4966.5 2310.70  4972.0 2310.23  4989.4 2305.03  4994.9 2304.21
  4998.0 2301.98  4998.2 2301.48  5001.7 2301.48  5002.0 2301.98  5011.2 2302.36
  5021.2 2305.70  5051.2 2309.65  5061.2 2311.59  5081.2 2313.77  5111.2 2318.35
  5141.2 2320.17  5151.2 2321.35  5161.2 2324.48  5171.2 2326.78  5211.2 2333.52
  5220.5 2335.82  5225.5 2338.59  5241.3 2341.64  5249.9 2343.74  5253.5 2343.74
#Mann=3,-1,0
  4877.1    0.16       0  4998.0    0.07       0  5002.0    0.16       0
Bank Sta=4998,5002
Exp/Cntr=0.3,0.1

Type RM Length L Ch R = 1,2335,59,59,59
BEGIN DESCRIPTION:
Elm 53 2335.251
END DESCRIPTION:
XS GIS Cut Line= 3
      1512110.09      6762896.36      1512253.95      6762977.57
      1512418.06      6763017.07
#Sta/Elev= 30
  4834.8 2322.16  4840.5 2322.16  4853.0 2318.98  4884.8 2315.76  4906.5 2312.58
  4912.2 2311.14  4933.9 2308.31  4949.8 2307.12  4955.5 2305.74  4971.4 2304.52
  4987.3 2300.20  4995.7 2299.66  4996.0 2299.16  4999.5 2299.16  4999.7 2299.66
  5003.1 2299.66  5011.4 2301.66  5019.9 2304.54  5025.0 2304.14  5052.5 2308.67
  5066.9 2310.41  5103.7 2317.53  5108.9 2317.96  5114.2 2320.27  5124.5 2321.04
  5134.8 2323.35  5150.8 2329.55  5156.0 2329.72  5164.7 2332.16  5168.8 2332.16
#Mann=3,-1,0
  4834.8    0.16       0  4995.7    0.07       0  4999.7    0.16       0
Bank Sta=4995.7,4999.7
Exp/Cntr=0.3,0.1

Type RM Length L Ch R = 1,2276,53,53,53
BEGIN DESCRIPTION:
Elm 53 2275.66
END DESCRIPTION:
XS GIS Cut Line= 3
      1512090.53      6762960.15      1512215.54      6763023.96
      1512387.43      6763059.12
#Sta/Elev= 30
  4856.2 2315.55  4872.4 2314.43  4886.9 2312.33  4909.1 2309.80  4925.7 2308.61
  4947.9 2304.94  4953.5 2303.46  4970.2 2301.89  4975.8 2299.86  4992.4 2299.65
  4993.5 2297.89  4993.7 2297.39  4997.2 2297.39  4997.5 2297.89  5006.2 2299.01
  5016.4 2299.73  5036.7 2303.13  5041.8 2303.17  5047.0 2303.79  5057.2 2306.72
  5067.4 2308.05  5077.7 2310.24  5087.2 2311.31  5098.1 2313.91  5108.3 2315.24
  5128.7 2319.09  5142.7 2319.75  5149.1 2322.96  5168.2 2328.46  5172.0 2328.46
#Mann=3,-1,0
  4856.2    0.16       0  4993.5    0.07       0  4997.5    0.16       0
Bank Sta=4993.5,4997.5
Exp/Cntr=0.3,0.1

Type RM Length L Ch R = 1,2223,63,63,63
BEGIN DESCRIPTION:
Elm 53 2222.79
END DESCRIPTION:
XS GIS Cut Line= 4
      1512025.46      6763005.74      1512179.08      6763061.72
      1512363.98      6763086.46      1512388.69      6763091.66
#Sta/Elev= 30
  4834.0 2313.25  4857.7 2311.74  4865.4 2309.69  4876.1 2308.71  4882.9 2308.94
  4888.2 2307.87  4913.5 2308.65  4918.8 2306.37  4938.7 2304.68  4944.1 2302.28
  4969.3 2295.16  4980.5 2294.54  4980.8 2294.04  4984.3 2294.04  4984.5 2294.54
  5007.8 2295.26  5013.6 2297.84  5023.7 2299.96  5033.7 2301.16  5064.0 2302.17
  5074.1 2303.04  5085.9 2305.85  5094.3 2308.84  5114.5 2313.47  5153.9 2319.43
  5158.9 2319.58  5182.0 2328.13  5187.1 2328.13  5204.9 2332.81  5209.3 2332.81
#Mann=3,-1,0
  4834.0    0.16       0  4980.5    0.07       0  4984.5    0.16       0
Bank Sta=4980.5,4984.5
Exp/Cntr=0.3,0.1

Type RM Length L Ch R = 1,2160,49,49,49
BEGIN DESCRIPTION:
Elm 53 2160.2
END DESCRIPTION:
XS GIS Cut Line= 3
      1511983.77      6763051.30      1512140.02      6763107.29
      1512337.93      6763109.90
#Sta/Elev= 30
  4836.9 2310.84  4868.2 2309.24  4873.5 2308.19  4880.7 2307.38  4891.3 2307.23
  4898.9 2306.61  4904.2 2305.12  4923.2 2303.72  4929.7 2301.81  4944.4 2299.02
  4960.4 2294.12  4963.7 2293.93  4964.0 2293.43  4967.5 2293.43  4967.7 2293.93
  4985.9 2293.97  5007.9 2294.65  5037.9 2296.80  5057.9 2299.21  5084.1 2301.19
  5087.9 2301.52  5097.9 2303.42  5137.9 2314.02  5147.9 2315.35  5157.9 2316.17
  5167.9 2317.66  5177.9 2319.74  5187.9 2319.91  5196.8 2320.95  5200.8 2320.95
#Mann=4,-1,0
  4836.9    0.16       0  4963.7    0.07       0  4967.7    0.16       0
  5084.1    0.07       0
Bank Sta=4963.7,4967.7
Exp/Cntr=0.3,0.1

Type RM Length L Ch R = 1,2111,64,64,64
BEGIN DESCRIPTION:
Elm 53 2111.06
END DESCRIPTION:
XS GIS Cut Line= 3
      1511935.61      6763087.77      1512098.35      6763141.15
      1512291.86      6763138.57
#Sta/Elev= 30
  4824.5 2313.24  4826.8 2313.24  4834.4 2312.24  4840.5 2312.31  4845.7 2311.29
  4855.4 2310.98  4866.0 2310.28  4872.3 2309.40  4877.6 2309.27  4897.5 2306.73
  4909.4 2304.96  4929.1 2302.71  4936.0 2301.67  4941.2 2301.87  4960.7 2300.20
  4965.8 2299.56  4966.0 2299.06  4969.5 2299.06  4969.8 2299.56  4973.1 2301.10
  5002.4 2300.07  5022.4 2300.18  5062.4 2301.50  5072.4 2302.39  5112.4 2307.83
  5142.4 2312.59  5162.4 2314.30  5172.4 2316.34  5182.4 2317.73  5189.3 2319.79
#Mann=3,-1,0
  4824.5    0.07       0  4965.8    0.07       0  4969.8    0.07       0
Bank Sta=4965.8,4969.8
Exp/Cntr=0.3,0.1

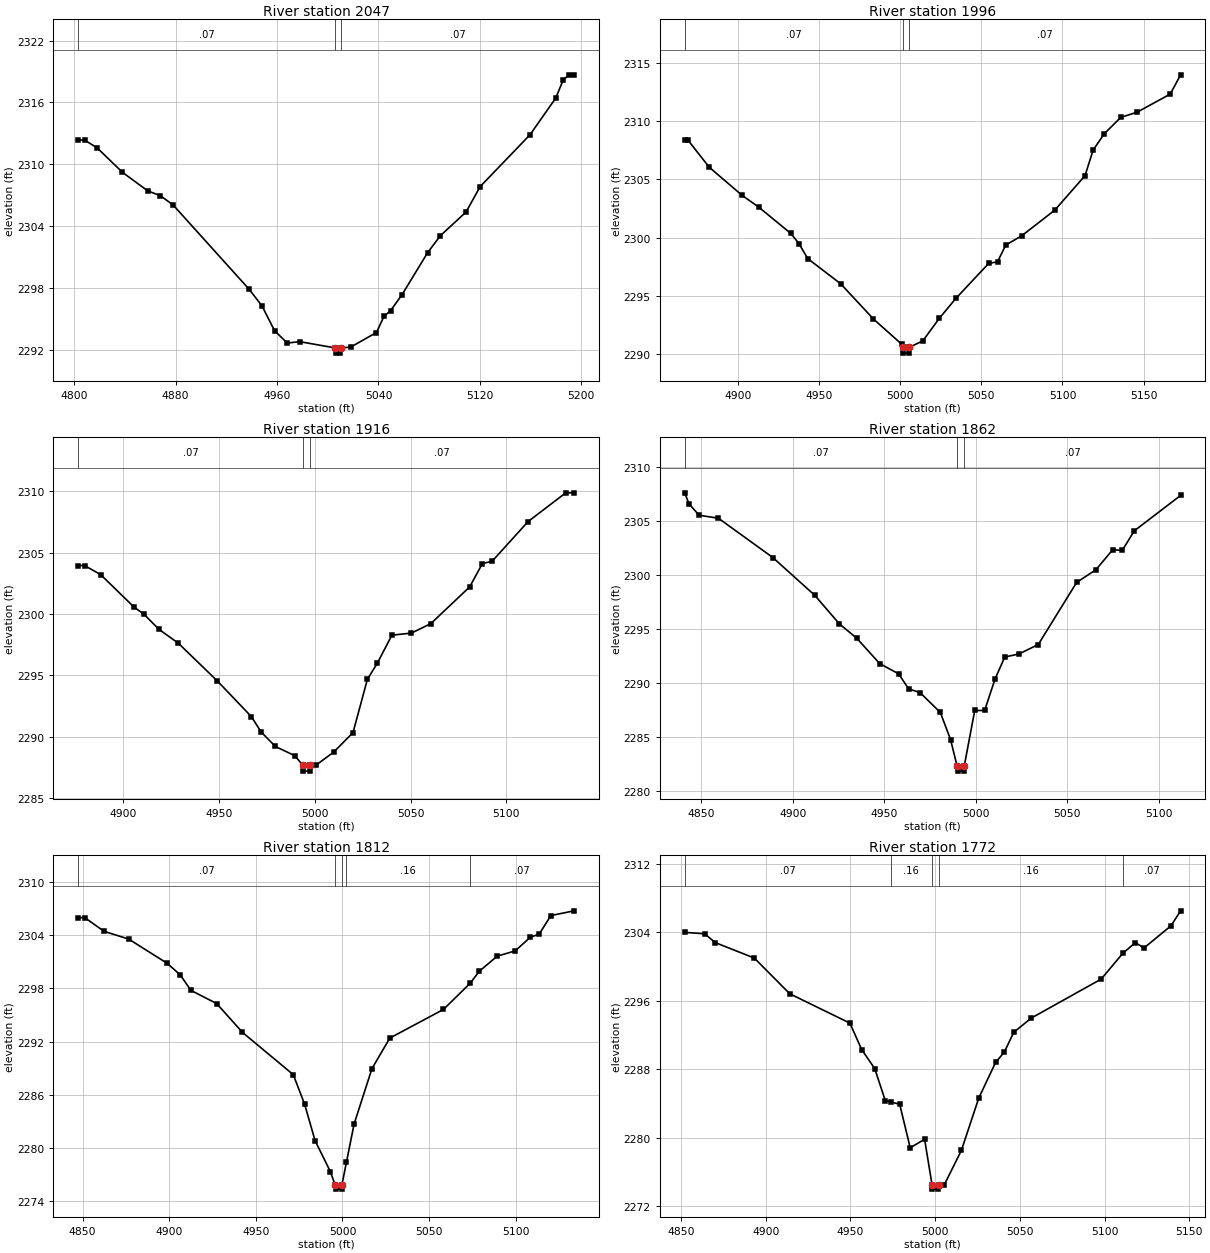
Type RM Length L Ch R = 1,2047,51,51,51
BEGIN DESCRIPTION:
Elm 53 2046.54
END DESCRIPTION:
XS GIS Cut Line= 3
      1511860.08      6763188.02      1512057.99      6763186.72
      1512249.43      6763214.07
#Sta/Elev= 30
  4803.1 2312.35  4808.1 2312.35  4818.0 2311.60  4838.0 2309.22  4858.0 2307.42
  4868.0 2306.95  4878.0 2306.05  4938.0 2297.87  4948.0 2296.28  4958.0 2293.86
  4968.0 2292.66  4978.0 2292.79  5006.1 2292.18  5006.3 2291.68  5009.8 2291.68
  5010.1 2292.18  5018.2 2292.27  5038.4 2293.68  5044.4 2295.26  5049.5 2295.79
  5058.6 2297.35  5078.8 2301.43  5088.9 2303.08  5109.1 2305.37  5120.2 2307.83
  5159.6 2312.87  5179.8 2316.41  5185.9 2318.22  5190.6 2318.68  5194.4 2318.68
#Mann=3,-1,0
  4803.1    0.07       0  5006.1    0.07       0  5010.1    0.07       0
Bank Sta=5006.1,5010.1
Exp/Cntr=0.3,0.1

Type RM Length L Ch R = 1,1996,80,80,80
BEGIN DESCRIPTION:
Elm 53 1995.93
END DESCRIPTION:
XS GIS Cut Line= 3
      1511890.05      6763202.35      1512025.44      6763223.18
      1512191.34      6763252.76
#Sta/Elev= 30
  4867.3 2308.34  4869.4 2308.34  4882.4 2306.04  4902.7 2303.62  4912.8 2302.63
  4932.7 2300.36  4937.7 2299.49  4943.1 2298.21  4963.4 2296.05  4983.6 2293.03
  5001.0 2290.87  5001.7 2290.61  5002.0 2290.11  5005.5 2290.11  5005.7 2290.61
  5014.0 2291.16  5024.2 2293.10  5034.3 2294.79  5054.6 2297.80  5060.0 2297.93
  5065.1 2299.37  5074.9 2300.16  5095.3 2302.36  5113.9 2305.31  5118.9 2307.50
  5125.7 2308.89  5135.9 2310.30  5146.0 2310.75  5166.4 2312.30  5172.8 2313.95
#Mann=3,-1,0
  4867.3    0.07       0  5001.7    0.07       0  5005.7    0.07       0
Bank Sta=5001.7,5005.7
Exp/Cntr=0.3,0.1

Type RM Length L Ch R = 1,1916,54,54,54
BEGIN DESCRIPTION:
Elm 53 1916.09
END DESCRIPTION:
XS GIS Cut Line= 3
      1511883.49      6763277.86      1512002.00      6763297.40
      1512138.69      6763320.83
#Sta/Elev= 30
  4876.6 2303.96  4879.9 2303.96  4888.3 2303.22  4905.8 2300.56  4910.9 2299.99
  4918.7 2298.76  4928.8 2297.63  4949.1 2294.56  4967.0 2291.63  4972.0 2290.39
  4979.5 2289.20  4989.6 2288.45  4993.7 2287.69  4993.9 2287.19  4997.4 2287.19
  4997.7 2287.69  5000.8 2287.69  5009.9 2288.74  5020.0 2290.33  5027.5 2294.68
  5032.6 2295.97  5040.3 2298.28  5050.5 2298.45  5060.6 2299.22  5080.9 2302.22
  5087.5 2304.12  5092.6 2304.31  5111.4 2307.55  5131.0 2309.89  5135.4 2309.89
#Mann=3,-1,0
  4876.6    0.07       0  4993.7    0.07       0  4997.7    0.07       0
Bank Sta=4993.7,4997.7
Exp/Cntr=0.3,0.1

Type RM Length L Ch R = 1,1862,50,50,50
BEGIN DESCRIPTION:
Elm 53 1862.19
END DESCRIPTION:
XS GIS Cut Line= 3
      1511848.32      6763281.76      1511994.19      6763349.48
      1512099.09      6763383.15
#Sta/Elev= 30
  4840.9 2307.63  4843.3 2306.60  4848.8 2305.55  4859.3 2305.28  4889.1 2301.63
  4912.0 2298.13  4925.4 2295.49  4934.9 2294.16  4947.5 2291.80  4957.8 2290.86
  4963.3 2289.46  4969.5 2289.12  4980.6 2287.28  4986.2 2284.76  4989.7 2282.34
  4990.0 2281.84  4993.5 2281.84  4993.7 2282.34  4999.4 2287.46  5004.8 2287.46
  5010.5 2290.38  5015.8 2292.41  5023.6 2292.70  5034.1 2293.57  5055.1 2299.33
  5065.6 2300.50  5074.8 2302.36  5080.0 2302.29  5086.6 2304.11  5111.9 2307.39
#Mann=3,-1,0
  4840.9    0.07       0  4989.7    0.07       0  4993.7    0.07       0
Bank Sta=4989.7,4993.7
Exp/Cntr=0.3,0.1

Type RM Length L Ch R = 1,1812,40,40,40
BEGIN DESCRIPTION:
Elm 53 1812.49
END DESCRIPTION:
XS GIS Cut Line= 3
      1511832.75      6763298.71      1511957.73      6763384.64
      1512087.93      6763418.49
#Sta/Elev= 30
  4847.5 2305.96  4851.3 2305.96  4862.4 2304.42  4876.6 2303.55  4898.8 2300.82
  4906.4 2299.51  4912.5 2297.77  4927.4 2296.28  4942.3 2293.03  4971.6 2288.27
  4978.1 2284.97  4984.2 2280.83  4993.0 2277.35  4995.7 2275.87  4996.0 2275.37
  4999.5 2275.37  4999.7 2275.87  5002.3 2278.41  5006.7 2282.70  5017.0 2288.94
  5027.3 2292.39  5058.3 2295.62  5073.7 2298.57  5079.0 2299.93  5089.3 2301.62
  5099.7 2302.22  5108.4 2303.75  5113.5 2304.10  5120.3 2306.20  5133.7 2306.73
#Mann=5,-1,0
  4847.5    0.07       0  4995.7    0.07       0  4999.7    0.07       0
  5002.3    0.16       0  5073.7    0.07       0
Bank Sta=4995.7,4999.7
Exp/Cntr=0.3,0.1

Type RM Length L Ch R = 1,1772,46,46,46
BEGIN DESCRIPTION:
Elm 53 1772.41
END DESCRIPTION:
XS GIS Cut Line= 3
      1511810.56      6763326.02      1511930.38      6763413.28
      1512070.54      6763448.32
#Sta/Elev= 30
  4852.2 2303.99  4864.0 2303.83  4870.2 2302.80  4893.3 2300.99  4914.2 2296.82
  4949.7 2293.39  4956.7 2290.29  4964.4 2288.06  4970.6 2284.33  4973.7 2284.18
  4979.1 2283.91  4985.3 2278.82  4993.8 2279.82  4998.2 2274.49  4998.4 2273.99
  5001.9 2273.99  5002.2 2274.49  5005.4 2274.49  5015.5 2278.51  5025.8 2284.65
  5035.7 2288.79  5040.9 2290.02  5046.4 2292.31  5056.7 2293.97  5098.0 2298.53
  5110.9 2301.57  5118.2 2302.79  5123.3 2302.17  5139.2 2304.76  5144.9 2306.51
#Mann=5,-1,0
  4852.2    0.07       0  4973.7    0.16       0  4998.2    0.07       0
  5002.2    0.16       0  5110.9    0.07       0
Bank Sta=4998.2,5002.2
Exp/Cntr=0.3,0.1