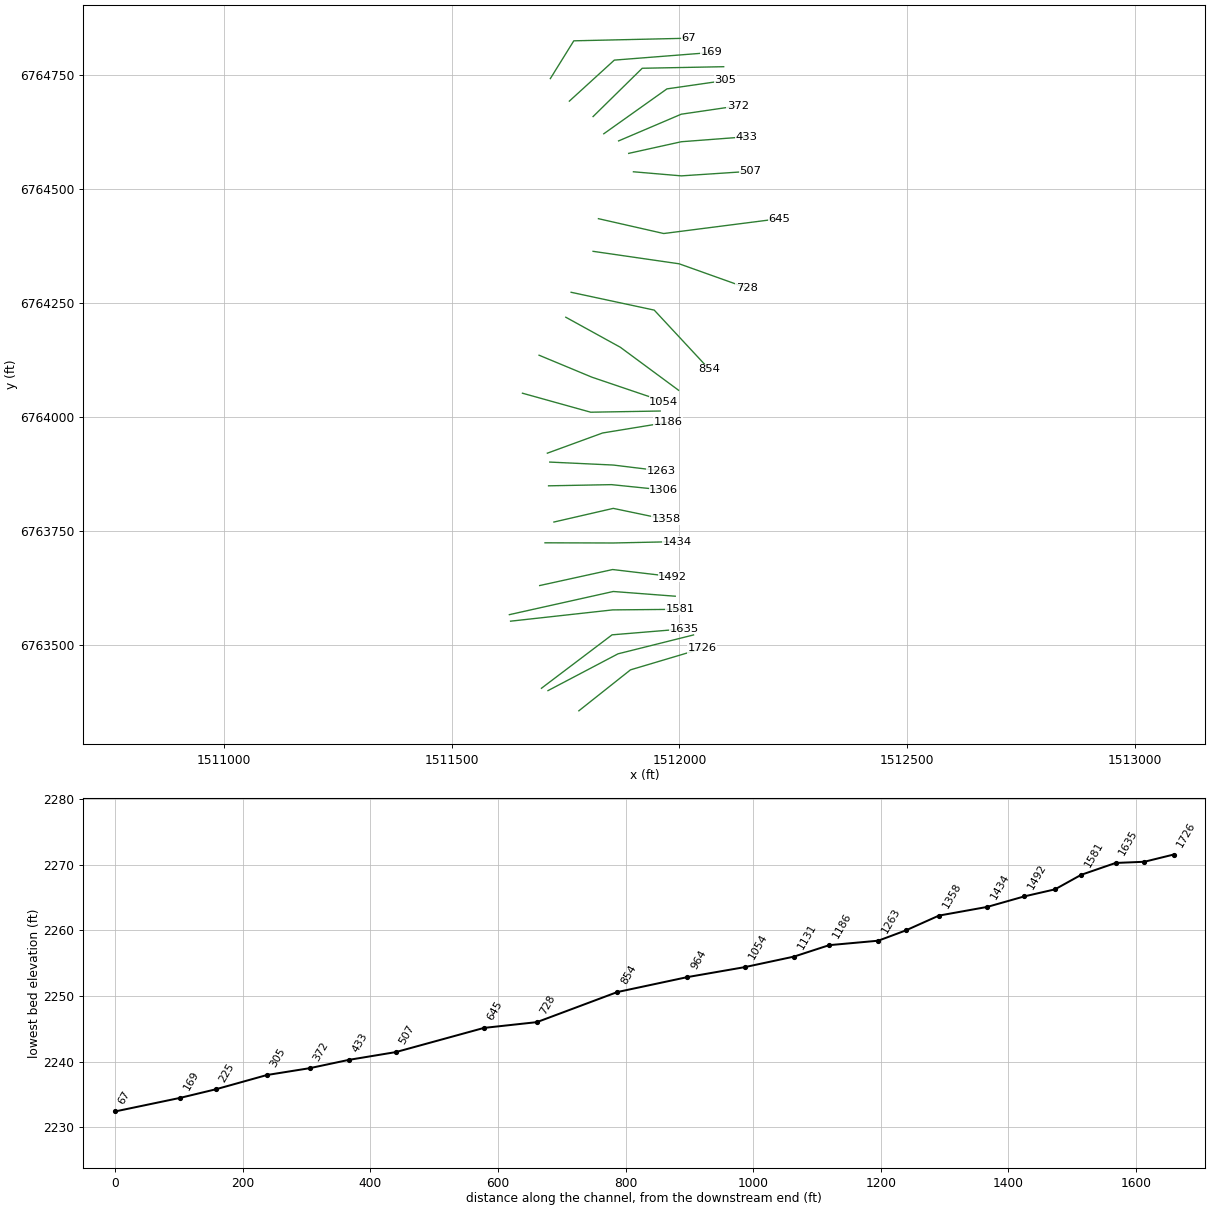
HEC-RAS study Elm 53.prj: Elm 53 Base Level Engineering

--- Elm 53.g01 (geometry) --- (continued)

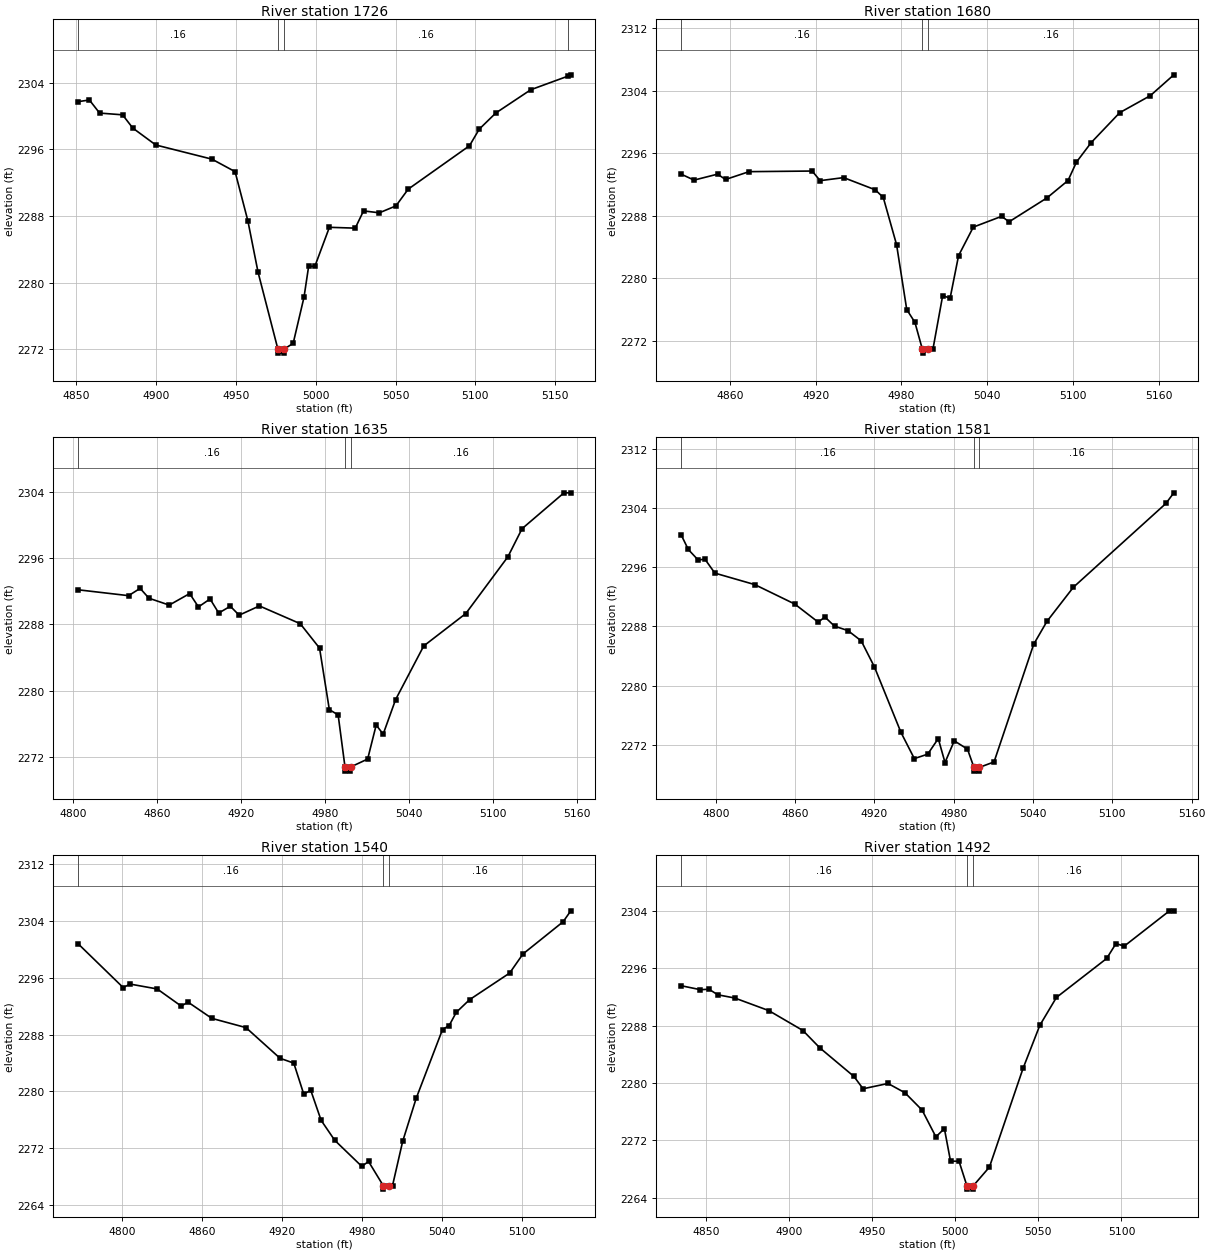
Type RM Length L Ch R = 1,1726,46,46,46
BEGIN DESCRIPTION:
Elm 53 1725.8
END DESCRIPTION:
XS GIS Cut Line= 3
      1511779.37      6763354.71      1511892.62      6763444.53
      1512050.06      6763491.37
#Sta/Elev= 30
  4851.0 2301.72  4858.1 2301.92  4864.5 2300.35  4878.9 2300.14  4885.3 2298.55
  4899.7 2296.52  4934.9 2294.82  4949.4 2293.32  4957.4 2287.43  4963.8 2281.25
  4976.2 2272.04  4976.5 2271.54  4980.0 2271.54  4980.2 2272.04  4985.8 2272.71
  4992.6 2278.26  4995.5 2281.96  4999.4 2281.96  5008.5 2286.64  5024.7 2286.54
  5029.9 2288.61  5039.8 2288.38  5050.2 2289.21  5057.9 2291.22  5096.3 2296.43
  5102.4 2298.42  5112.8 2300.36  5134.7 2303.15  5157.8 2304.77  5159.8 2304.94
#Mann=4,-1,0
  4851.0    0.16       0  4976.2    0.07       0  4980.2    0.16       0
  5157.8    0.07       0
Bank Sta=4976.2,4980.2
Exp/Cntr=0.3,0.1

Type RM Length L Ch R = 1,1680,45,45,45
BEGIN DESCRIPTION:
Elm 53 1679.55
END DESCRIPTION:
XS GIS Cut Line= 3
      1511711.65      6763398.97      1511865.28      6763479.69
      1512030.93      6763521.10
#Sta/Elev= 30
  4826.0 2293.33  4835.1 2292.56  4851.5 2293.32  4857.1 2292.64  4873.5 2293.64
  4917.6 2293.72  4923.2 2292.49  4939.6 2292.88  4961.7 2291.32  4967.3 2290.34
  4976.6 2284.30  4983.7 2276.01  4989.4 2274.38  4994.6 2270.94  4994.8 2270.44
  4998.6 2270.94  5002.0 2270.94  5008.8 2277.79  5014.0 2277.47  5019.9 2282.90
  5030.2 2286.55  5050.0 2287.93  5055.2 2287.23  5081.7 2290.29  5096.4 2292.51
  5102.3 2294.87  5112.6 2297.36  5132.5 2301.18  5153.9 2303.36  5170.3 2306.02
#Mann=3,-1,0
  4826.0    0.16       0  4994.6    0.07       0  4998.6    0.16       0
Bank Sta=4994.6,4998.6
Exp/Cntr=0.3,0.1

Type RM Length L Ch R = 1,1635,54,54,54
BEGIN DESCRIPTION:
Elm 53 1635.19
END DESCRIPTION:
XS GIS Cut Line= 3
      1511697.30      6763404.16      1511852.26      6763521.35
      1512009.83      6763534.38
#Sta/Elev= 30
  4803.3 2292.18  4839.4 2291.47  4847.7 2292.35  4854.0 2291.16  4868.5 2290.33
  4883.1 2291.72  4889.4 2290.11  4897.7 2291.07  4903.9 2289.37  4912.2 2290.19
  4918.5 2289.11  4933.0 2290.23  4962.2 2288.08  4976.0 2285.13  4983.0 2277.70
  4989.3 2277.05  4994.2 2270.76  4994.4 2270.26  4997.9 2270.26  4998.2 2270.76
  5010.4 2271.72  5016.5 2275.83  5021.5 2274.73  5030.4 2278.91  5050.5 2285.39
  5080.6 2289.31  5110.7 2296.17  5120.8 2299.56  5150.8 2303.90  5155.7 2303.90
#Mann=3,-1,0
  4803.3    0.16       0  4994.2    0.07       0  4998.2    0.16       0
Bank Sta=4994.2,4998.2
Exp/Cntr=0.3,0.1

Type RM Length L Ch R = 1,1581,41,41,41
BEGIN DESCRIPTION:
Elm 53 1580.68
END DESCRIPTION:
XS GIS Cut Line= 3
      1511629.57      6763551.30      1511853.56      6763576.04
      1512001.00      6763577.33
#Sta/Elev= 30
  4773.7 2300.38  4779.2 2298.37  4786.7 2296.94  4791.7 2297.08  4799.3 2295.18
  4829.5 2293.63  4859.7 2291.01  4877.5 2288.56  4882.5 2289.26  4889.8 2288.02
  4899.9 2287.43  4910.0 2286.04  4920.0 2282.52  4940.1 2273.67  4950.2 2270.14
  4960.3 2270.74  4968.3 2272.84  4973.4 2269.61  4980.4 2272.54  4990.4 2271.42
  4995.3 2268.95  4995.5 2268.45  4999.0 2268.45  4999.3 2268.95  5010.5 2269.69
  5040.5 2285.58  5050.5 2288.66  5070.5 2293.27  5140.5 2304.58  5146.5 2306.02
#Mann=3,-1,0
  4773.7    0.16       0  4995.3    0.07       0  4999.3    0.16       0
Bank Sta=4995.3,4999.3
Exp/Cntr=0.3,0.1

Type RM Length L Ch R = 1,1540,48,48,48
BEGIN DESCRIPTION:
Elm 53 1540.41
END DESCRIPTION:
XS GIS Cut Line= 3
      1511626.98      6763565.62      1511854.86      6763616.41
      1511990.80      6763606.05
#Sta/Elev= 30
  4766.9 2300.79  4800.8 2294.61  4805.9 2295.11  4826.3 2294.42  4844.3 2292.01
  4849.4 2292.57  4867.3 2290.28  4892.9 2288.98  4918.5 2284.66  4928.8 2283.98
  4936.3 2279.60  4941.5 2280.17  4949.3 2275.93  4959.5 2273.12  4979.8 2269.45
  4984.9 2270.13  4995.9 2266.74  4996.1 2266.24  4999.9 2266.74  5002.9 2266.74
  5010.5 2272.96  5020.6 2279.00  5040.4 2288.71  5045.4 2289.27  5050.7 2291.12
  5060.7 2292.91  5090.8 2296.66  5100.8 2299.35  5130.9 2303.88  5136.7 2305.42
#Mann=3,-1,0
  4766.9    0.16       0  4995.9    0.07       0  4999.9    0.16       0
Bank Sta=4995.9,4999.9
Exp/Cntr=0.3,0.1

Type RM Length L Ch R = 1,1492,58,58,58
BEGIN DESCRIPTION:
Elm 53 1492.26
END DESCRIPTION:
XS GIS Cut Line= 3
      1511693.42      6763629.43      1511853.56      6763664.58
      1511985.08      6763648.96
#Sta/Elev= 30
  4835.1 2293.59  4846.8 2293.03  4851.9 2293.10  4857.2 2292.32  4867.4 2291.87
  4887.9 2290.11  4908.4 2287.33  4918.6 2284.90  4939.1 2280.91  4944.6 2279.19
  4959.6 2279.93  4969.8 2278.63  4980.1 2276.21  4988.4 2272.47  4993.5 2273.63
  4997.2 2269.07  5002.3 2269.07  5007.0 2265.67  5007.3 2265.17  5010.8 2265.17
  5011.0 2265.67  5020.6 2268.25  5040.8 2282.03  5050.9 2288.05  5060.9 2291.95
  5091.1 2297.39  5096.7 2299.47  5101.7 2299.12  5128.9 2304.05  5131.5 2304.05
#Mann=3,-1,0
  4835.1    0.16       0  5007.0    0.07       0  5011.0    0.16       0
Bank Sta=5007,5011
Exp/Cntr=0.3,0.1

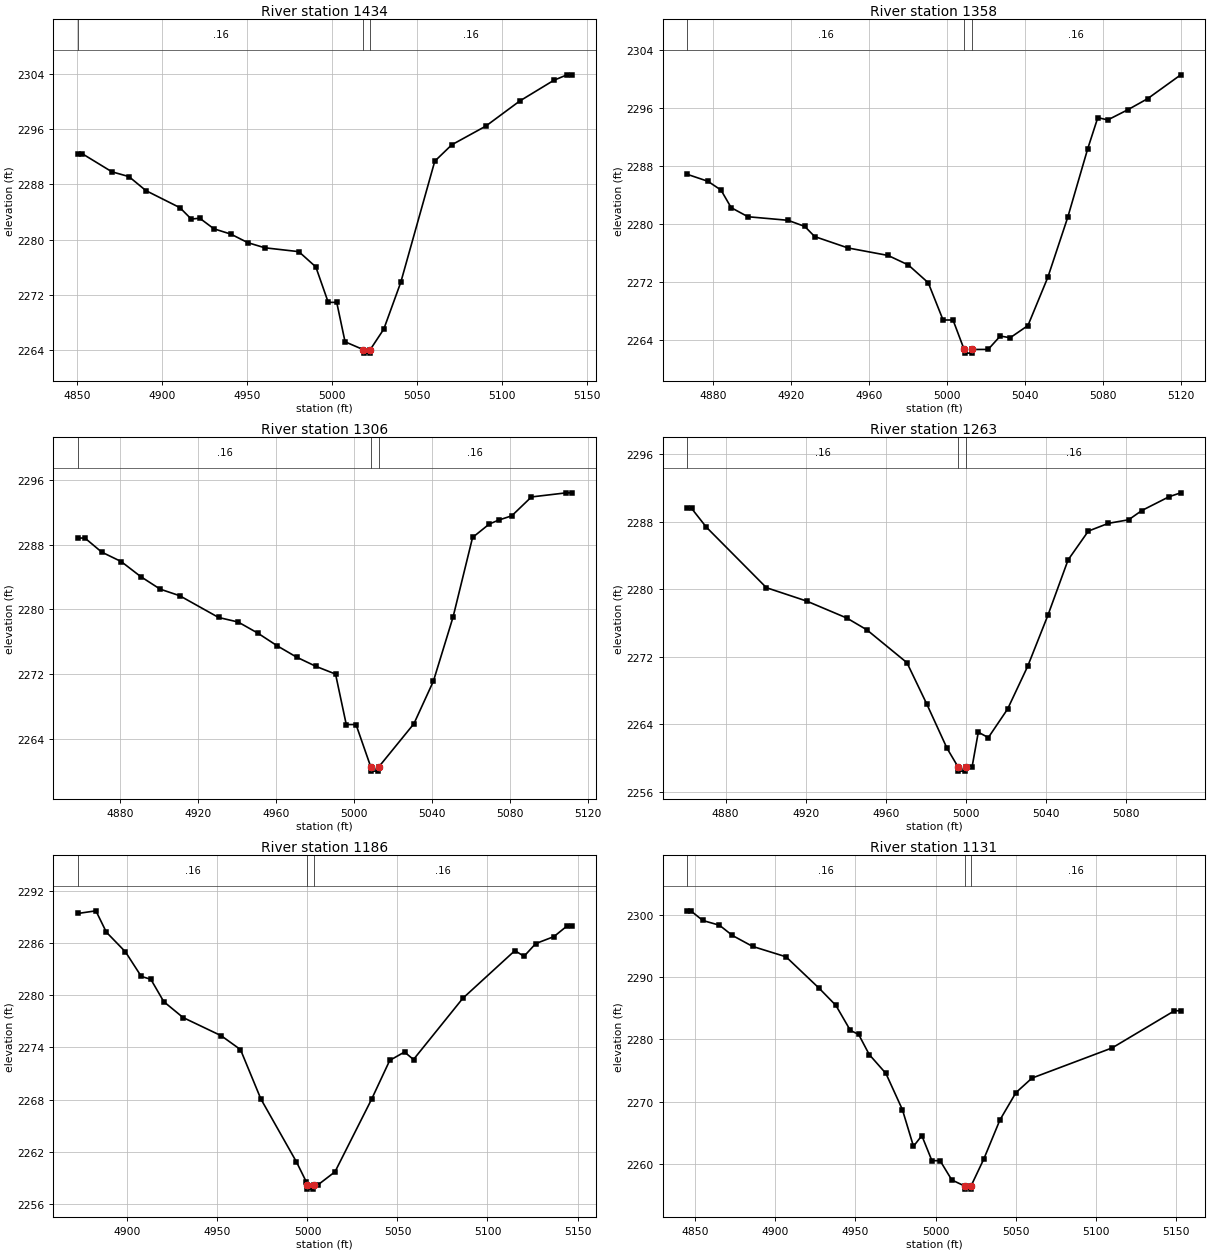
Type RM Length L Ch R = 1,1434,76,76,76
BEGIN DESCRIPTION:
Elm 53 1433.941
END DESCRIPTION:
XS GIS Cut Line= 3
      1511705.09      6763723.18      1511854.49      6763722.79
      1511995.46      6763725.78
#Sta/Elev= 30
  4850.6 2292.43  4853.1 2292.43  4870.5 2289.82  4880.5 2289.13  4890.5 2287.10
  4910.5 2284.63  4917.2 2282.98  4922.2 2283.10  4930.5 2281.57  4940.5 2280.80
  4950.5 2279.56  4960.5 2278.82  4980.5 2278.26  4990.5 2276.05  4997.8 2270.92
  5002.8 2270.92  5007.7 2265.21  5018.5 2264.07  5018.8 2263.57  5022.3 2263.57
  5022.5 2264.07  5030.5 2267.05  5040.5 2273.83  5060.5 2291.36  5070.5 2293.73
  5090.5 2296.43  5110.5 2300.07  5130.5 2303.06  5138.3 2303.86  5141.0 2303.86
#Mann=3,-1,0
  4850.6    0.16       0  5018.5    0.07       0  5022.5    0.16       0
Bank Sta=5018.5,5022.5
Exp/Cntr=0.3,0.1

Type RM Length L Ch R = 1,1358,52,52,52
BEGIN DESCRIPTION:
Elm 53 1358.12
END DESCRIPTION:
XS GIS Cut Line= 3
      1511724.68      6763768.75      1511854.86      6763798.70
      1511971.66      6763774.31
#Sta/Elev= 30
  4866.8 2286.86  4877.4 2285.90  4884.1 2284.69  4889.3 2282.27  4897.9 2281.02
  4918.4 2280.53  4927.0 2279.69  4932.1 2278.29  4949.2 2276.72  4969.7 2275.69
  4980.1 2274.38  4990.3 2271.93  4997.9 2266.80  5003.0 2266.80  5008.7 2262.74
  5009.0 2262.24  5012.5 2262.24  5012.7 2262.74  5021.0 2262.75  5027.2 2264.59
  5032.3 2264.36  5041.4 2266.04  5051.6 2272.69  5061.8 2280.95  5072.0 2290.36
  5077.2 2294.67  5082.3 2294.35  5092.5 2295.74  5102.7 2297.27  5119.7 2300.56
#Mann=3,-1,0
  4866.8    0.16       0  5008.7    0.07       0  5012.7    0.16       0
Bank Sta=5008.7,5012.7
Exp/Cntr=0.3,0.1

Type RM Length L Ch R = 1,1306,43,43,43
BEGIN DESCRIPTION:
Elm 53 1306.31
END DESCRIPTION:
XS GIS Cut Line= 3
      1511712.93      6763848.18      1511850.96      6763850.78
      1511965.50      6763839.07
#Sta/Elev= 30
  4858.4 2288.85  4861.9 2288.85  4870.5 2287.11  4880.5 2285.94  4890.5 2284.08
  4900.5 2282.52  4910.5 2281.71  4930.5 2279.01  4940.5 2278.45  4950.5 2277.09
  4960.5 2275.51  4970.5 2274.10  4980.5 2272.95  4990.5 2272.00  4996.0 2265.75
  5001.0 2265.75  5008.6 2260.48  5008.8 2259.98  5012.3 2259.98  5012.6 2260.48
  5030.7 2265.85  5040.7 2271.12  5050.8 2279.07  5060.8 2288.92  5069.4 2290.59
  5074.4 2291.09  5080.9 2291.60  5091.0 2293.94  5108.9 2294.45  5111.6 2294.45
#Mann=3,-1,0
  4858.4    0.16       0  5008.6    0.07       0  5012.6    0.16       0
Bank Sta=5008.6,5012.6
Exp/Cntr=0.3,0.1

Type RM Length L Ch R = 1,1263,77,77,77
BEGIN DESCRIPTION:
Elm 53 1262.97
END DESCRIPTION:
XS GIS Cut Line= 3
      1511715.53      6763900.26      1511854.86      6763893.75
      1511960.79      6763880.83
#Sta/Elev= 27
  4860.9 2289.59  4863.1 2289.59  4870.4 2287.38  4900.4 2280.19  4920.4 2278.61
  4940.5 2276.59  4950.5 2275.19  4970.5 2271.29  4980.5 2266.33  4990.5 2261.13
  4996.0 2258.92  4996.2 2258.42  4999.7 2258.42  5000.0 2258.92  5003.0 2258.92
  5006.1 2263.04  5011.1 2262.40  5020.7 2265.78  5030.7 2270.84  5040.8 2276.90
  5050.9 2283.49  5061.0 2286.91  5071.0 2287.83  5081.1 2288.25  5087.7 2289.35
  5101.3 2290.99  5107.1 2291.45
#Mann=3,-1,0
  4860.9    0.16       0  4996.0    0.07       0  5000.0    0.16       0
Bank Sta=4996,5000
Exp/Cntr=0.3,0.1

Type RM Length L Ch R = 1,1186,55,55,55
BEGIN DESCRIPTION:
Elm 53 1185.57
END DESCRIPTION:
XS GIS Cut Line= 3
      1511710.29      6763919.78      1511831.42      6763964.06
      1511974.64      6763987.50
#Sta/Elev= 30
  4872.6 2289.39  4882.5 2289.69  4888.3 2287.24  4898.9 2284.98  4907.7 2282.16
  4913.0 2281.83  4920.2 2279.26  4930.9 2277.44  4952.1 2275.35  4962.8 2273.76
  4974.1 2268.10  4993.9 2260.86  4999.3 2258.60  4999.6 2258.24  4999.8 2257.74
  5003.3 2257.74  5003.6 2258.24  5005.9 2258.24  5015.3 2259.73  5035.6 2268.05
  5045.7 2272.52  5053.9 2273.48  5058.9 2272.62  5086.3 2279.65  5115.2 2285.12
  5120.3 2284.47  5126.8 2285.93  5136.9 2286.73  5144.4 2287.99  5146.7 2287.99
#Mann=3,-1,0
  4872.6    0.16       0  4999.6    0.07       0  5003.6    0.16       0
Bank Sta=4999.6,5003.6
Exp/Cntr=0.3,0.1

Type RM Length L Ch R = 1,1131,77,77,77
BEGIN DESCRIPTION:
Elm 53 1131.38
END DESCRIPTION:
XS GIS Cut Line= 3
      1511655.66      6764051.30      1511805.38      6764009.64
      1511957.75      6764012.24
#Sta/Elev= 30
  4845.1 2300.62  4847.3 2300.62  4854.8 2299.07  4865.2 2298.31  4873.2 2296.68
  4885.9 2294.91  4906.7 2293.25  4927.5 2288.17  4937.8 2285.46  4946.8 2281.46
  4952.0 2280.80  4958.6 2277.58  4969.0 2274.55  4979.3 2268.74  4986.2 2262.86
  4991.4 2264.58  4997.7 2260.56  5002.8 2260.56  5010.1 2257.47  5018.1 2256.50
  5018.4 2256.00  5021.9 2256.00  5022.1 2256.50  5030.1 2260.85  5040.1 2267.08
  5050.1 2271.47  5060.1 2273.80  5110.1 2278.64  5149.0 2284.60  5152.9 2284.60
#Mann=3,-1,0
  4845.1    0.16       0  5018.1    0.07       0  5022.1    0.16       0
Bank Sta=5018.1,5022.1
Exp/Cntr=0.3,0.1

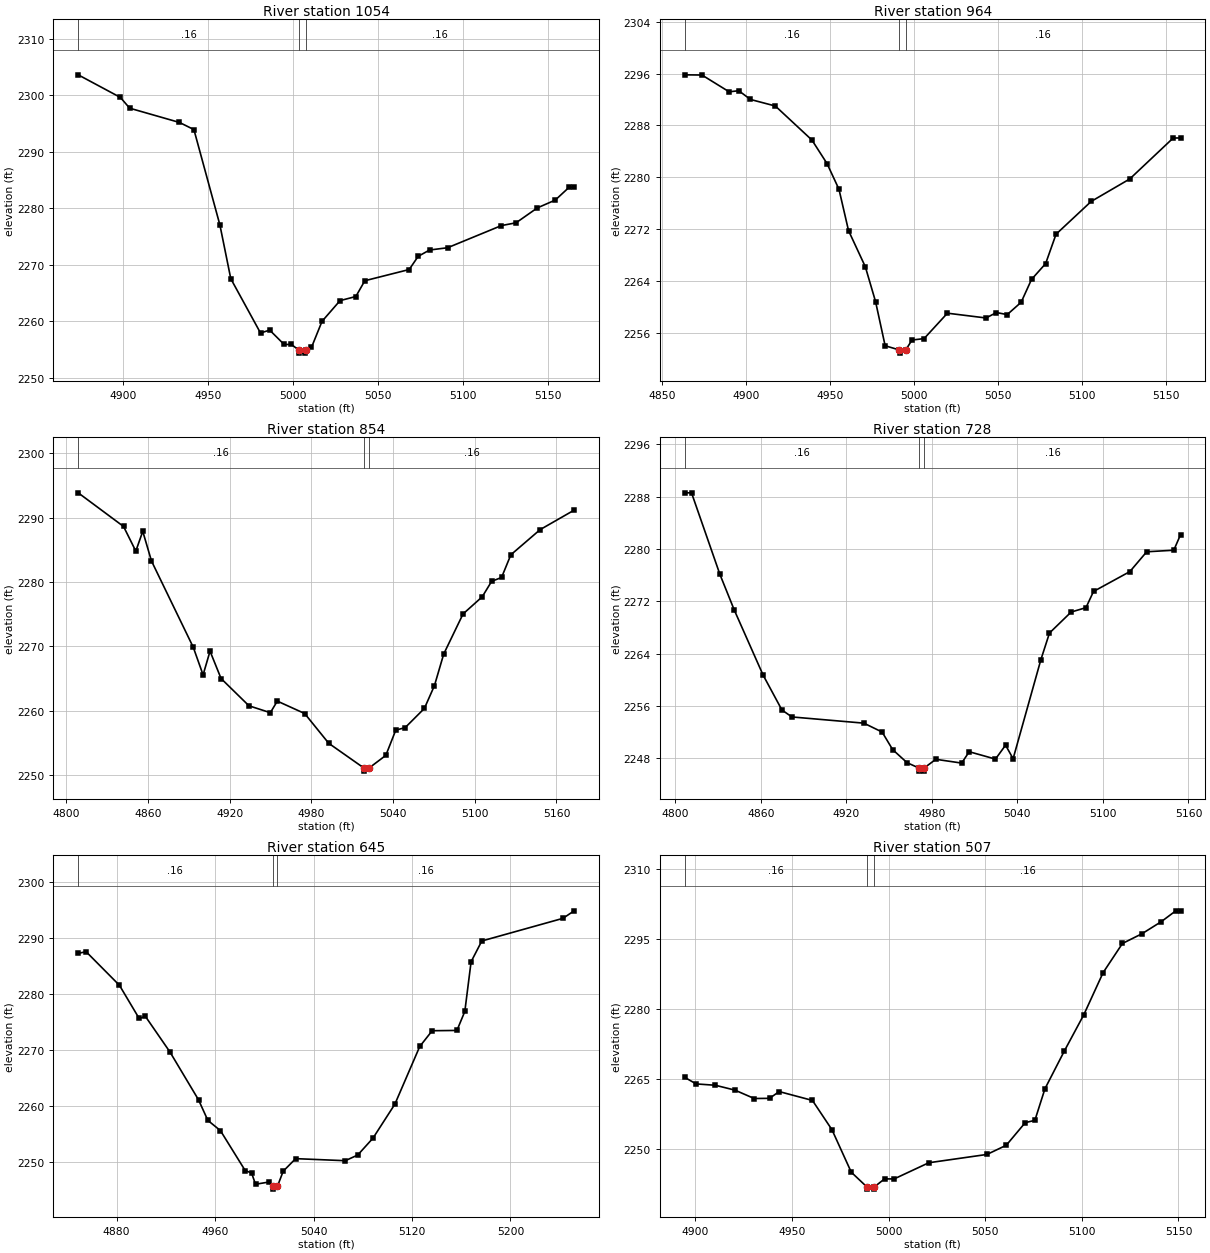
Type RM Length L Ch R = 1,1054,90,90,90
BEGIN DESCRIPTION:
Elm 53 1054.4
END DESCRIPTION:
XS GIS Cut Line= 3
      1511692.07      6764134.65      1511807.99      6764086.46
      1511965.55      6764033.07
#Sta/Elev= 30
  4873.5 2303.60  4898.3 2299.61  4903.8 2297.70  4933.1 2295.18  4941.6 2293.92
  4956.9 2277.05  4963.3 2267.56  4980.8 2257.96  4986.2 2258.47  4994.7 2255.93
  4999.0 2255.93  5003.5 2254.90  5003.7 2254.40  5007.2 2254.40  5007.5 2254.90
  5010.8 2255.41  5017.0 2260.02  5027.6 2263.68  5036.9 2264.41  5042.2 2267.20
  5068.3 2269.18  5073.6 2271.51  5080.3 2272.63  5090.9 2273.03  5122.6 2276.95
  5131.2 2277.44  5143.7 2280.07  5154.3 2281.46  5162.5 2283.74  5165.4 2283.74
#Mann=3,-1,0
  4873.5    0.16       0  5003.5    0.07       0  5007.5    0.16       0
Bank Sta=5003.5,5007.5
Exp/Cntr=0.3,0.1

Type RM Length L Ch R = 1,964,110,110,110
BEGIN DESCRIPTION:
Elm 53 963.814
END DESCRIPTION:
XS GIS Cut Line= 3
      1511750.70      6764217.97      1511870.36      6764152.09
      1511998.13      6764057.78
#Sta/Elev= 30
  4863.4 2295.80  4873.7 2295.77  4889.9 2293.18  4895.6 2293.35  4902.6 2292.00
  4917.4 2290.99  4939.2 2285.74  4948.2 2282.11  4955.3 2278.15  4961.0 2271.77
  4971.0 2266.20  4977.1 2260.82  4982.8 2254.02  4991.1 2253.38  4991.4 2252.88
  4995.1 2253.38  4998.8 2254.90  5006.0 2255.12  5019.9 2259.04  5042.9 2258.30
  5049.1 2259.14  5055.5 2258.82  5063.8 2260.72  5070.0 2264.25  5078.4 2266.69
  5084.6 2271.22  5105.5 2276.27  5128.5 2279.74  5154.4 2286.06  5158.8 2286.06
#Mann=3,-1,0
  4863.4    0.16       0  4991.1    0.07       0  4995.1    0.16       0
Bank Sta=4991.1,4995.1
Exp/Cntr=0.3,0.1

Type RM Length L Ch R = 1,854,126,126,126
BEGIN DESCRIPTION:
Elm 53 853.78
END DESCRIPTION:
XS GIS Cut Line= 3
      1511762.42      6764272.66      1511944.71      6764233.59
      1512065.77      6764103.42
#Sta/Elev= 30
  4808.8 2293.84  4842.1 2288.61  4851.1 2284.78  4856.2 2287.86  4862.6 2283.25
  4893.3 2269.84  4900.5 2265.55  4905.6 2269.24  4913.7 2264.99  4934.2 2260.75
  4949.9 2259.68  4955.0 2261.48  4975.1 2259.55  4992.8 2254.92  5018.5 2251.10
  5018.8 2250.60  5022.5 2251.10  5034.7 2253.05  5042.0 2256.97  5048.9 2257.36
  5063.0 2260.34  5070.4 2263.88  5077.2 2268.79  5091.4 2275.02  5105.5 2277.69
  5112.4 2280.09  5119.7 2280.69  5126.5 2284.21  5148.0 2288.12  5173.0 2291.15
#Mann=3,-1,0
  4808.8    0.16       0  5018.5    0.07       0  5022.5    0.16       0
Bank Sta=5018.5,5022.5
Exp/Cntr=0.3,0.1

Type RM Length L Ch R = 1,728,83,83,83
BEGIN DESCRIPTION:
Elm 53 728.19
END DESCRIPTION:
XS GIS Cut Line= 3
      1511810.57      6764362.50      1511999.39      6764335.16
      1512147.38      6764282.40
#Sta/Elev= 30
  4806.6 2288.60  4811.4 2288.60  4831.3 2276.13  4841.4 2270.66  4861.6 2260.72
  4874.8 2255.38  4881.8 2254.31  4932.3 2253.36  4945.1 2252.00  4952.5 2249.31
  4962.6 2247.31  4970.7 2246.52  4971.0 2246.02  4974.5 2246.02  4974.7 2246.52
  4982.8 2247.83  5000.9 2247.25  5006.2 2248.99  5024.6 2247.86  5031.7 2249.99
  5037.0 2247.92  5056.4 2263.02  5062.5 2267.15  5077.7 2270.36  5088.1 2271.03
  5093.4 2273.51  5118.9 2276.55  5130.7 2279.58  5149.7 2279.82  5154.5 2282.22
#Mann=3,-1,0
  4806.6    0.16       0  4970.7    0.07       0  4974.7    0.16       0
Bank Sta=4970.7,4974.7
Exp/Cntr=0.3,0.1

Type RM Length L Ch R = 1,645,138,138,138
BEGIN DESCRIPTION:
Elm 53 645.15
END DESCRIPTION:
XS GIS Cut Line= 3
      1511822.34      6764434.11      1511965.54      6764401.56
      1512219.41      6764434.11
#Sta/Elev= 30
  4848.9 2287.20  4855.3 2287.50  4882.4 2281.50  4898.4 2275.59  4903.5 2275.95
  4923.4 2269.61  4946.6 2261.08  4954.2 2257.40  4964.4 2255.58  4984.5 2248.46
  4989.7 2248.02  4992.9 2246.01  5003.7 2246.40  5006.7 2245.64  5006.9 2245.14
  5010.7 2245.64  5015.4 2248.34  5025.5 2250.58  5065.8 2250.21  5075.9 2251.22
  5088.3 2254.23  5106.1 2260.30  5126.3 2270.59  5136.4 2273.40  5156.5 2273.45
  5162.9 2276.84  5168.0 2285.71  5176.7 2289.41  5242.6 2293.45  5251.7 2294.79
#Mann=3,-1,0
  4848.9    0.16       0  5006.7    0.07       0  5010.7    0.16       0
Bank Sta=5006.7,5010.7
Exp/Cntr=0.3,0.1

Type RM Length L Ch R = 1,507,74,74,74
BEGIN DESCRIPTION:
Elm 53 507.467
END DESCRIPTION:
XS GIS Cut Line= 3
      1511899.12      6764536.98      1512004.23      6764528.01
      1512155.00      6764538.00
#Sta/Elev= 30
  4894.5 2265.41  4900.4 2264.00  4910.4 2263.71  4920.5 2262.67  4930.5 2260.87
  4938.4 2260.91  4943.4 2262.36  4960.6 2260.46  4970.7 2254.19  4980.7 2245.08
  4988.7 2241.96  4989.0 2241.46  4992.5 2241.46  4992.7 2241.96  4997.9 2243.65
  5002.9 2243.65  5020.8 2247.11  5050.9 2248.89  5060.9 2250.86  5070.7 2255.70
  5075.7 2256.20  5080.9 2262.96  5091.0 2271.10  5101.0 2278.81  5111.0 2287.84
  5121.0 2294.09  5131.1 2296.17  5141.1 2298.76  5148.6 2301.08  5151.1 2301.08
#Mann=3,-1,0
  4894.5    0.16       0  4988.7    0.07       0  4992.7    0.16       0
Bank Sta=4988.7,4992.7
Exp/Cntr=0.3,0.1

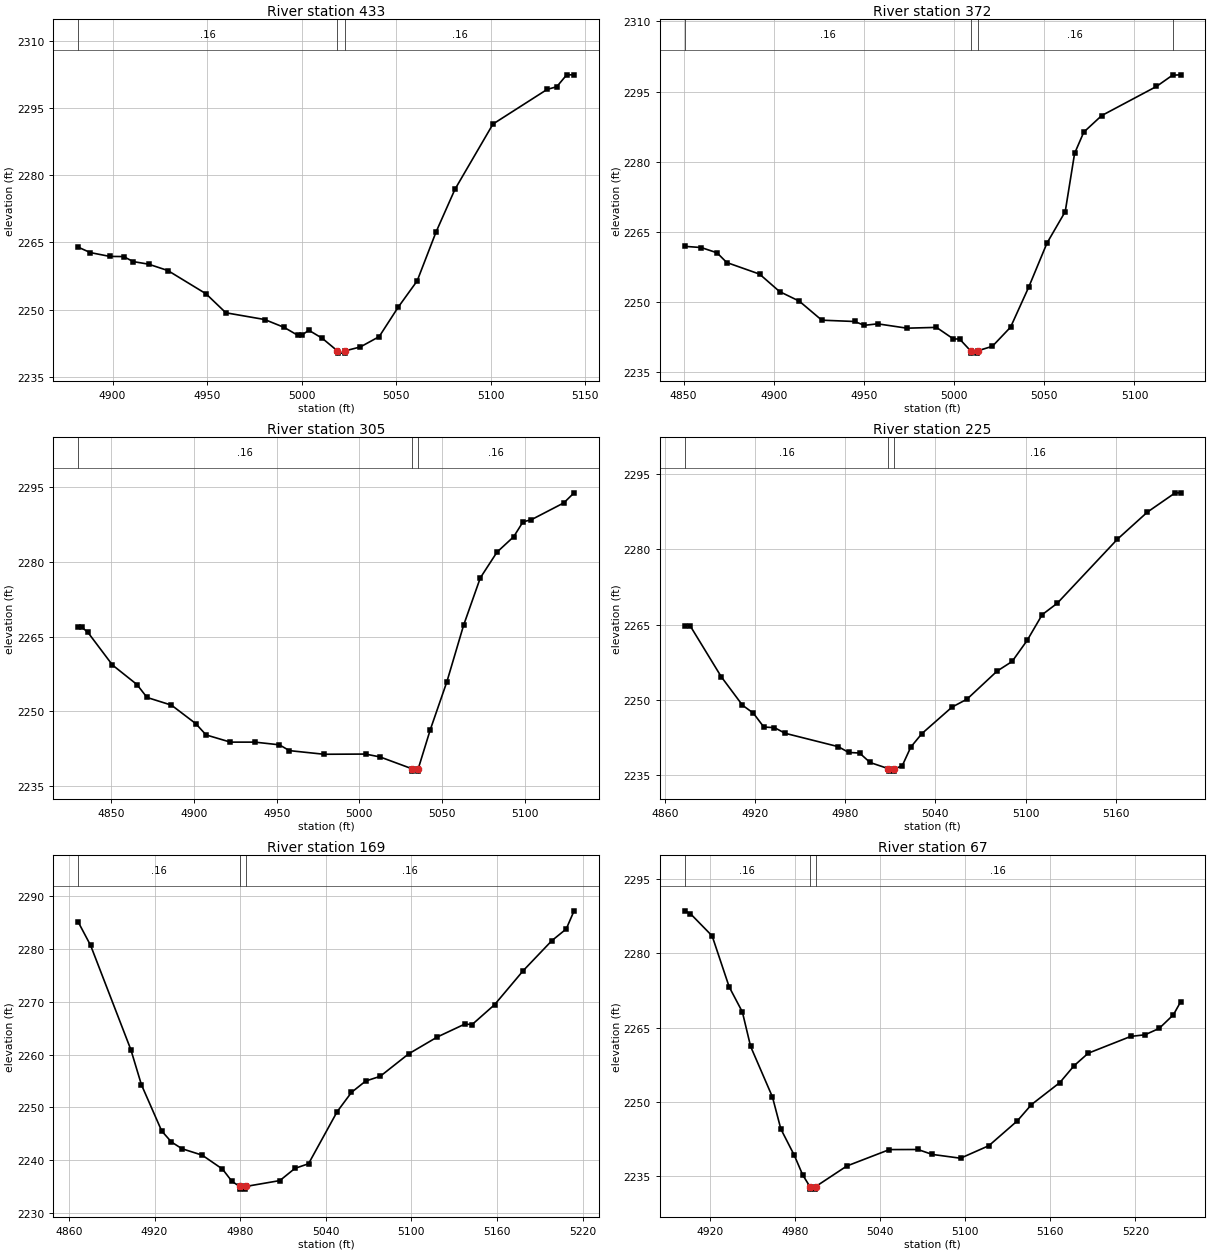
Type RM Length L Ch R = 1,433,61,61,61
BEGIN DESCRIPTION:
Elm 53 5225
END DESCRIPTION:
XS GIS Cut Line= 3
      1511888.71      6764577.34      1512004.12      6764602.87
      1512147.81      6764613.80
#Sta/Elev= 30
  4881.8 2263.91  4888.2 2262.70  4898.5 2261.85  4905.8 2261.81  4910.9 2260.69
  4919.0 2260.12  4929.2 2258.70  4949.4 2253.51  4959.9 2249.27  4980.4 2247.77
  4990.7 2246.02  4997.9 2244.26  5000.0 2244.26  5003.8 2245.37  5010.9 2243.58
  5018.9 2240.77  5019.2 2240.27  5022.7 2240.27  5022.9 2240.77  5031.0 2241.64
  5041.0 2243.95  5051.0 2250.48  5061.1 2256.39  5071.1 2267.31  5081.1 2276.83
  5101.2 2291.38  5129.9 2299.12  5134.9 2299.69  5140.2 2302.36  5144.1 2302.36
#Mann=3,-1,0
  4881.8    0.16       0  5018.9    0.07       0  5022.9    0.16       0
Bank Sta=5018.9,5022.9
Exp/Cntr=0.3,0.1

Type RM Length L Ch R = 1,372,67,67,67
BEGIN DESCRIPTION:
Elm 53 5224
END DESCRIPTION:
XS GIS Cut Line= 3
      1511866.60      6764604.70      1512004.04      6764663.28
      1512128.31      6764681.51
#Sta/Elev= 30
  4850.6 2261.86  4859.7 2261.61  4868.5 2260.48  4873.9 2258.40  4892.1 2255.92
  4903.2 2252.18  4914.1 2250.14  4926.6 2246.06  4944.8 2245.78  4950.2 2244.96
  4957.6 2245.28  4973.8 2244.35  4990.2 2244.52  4999.6 2242.04  5003.0 2242.04
  5009.1 2239.51  5009.3 2239.01  5012.8 2239.01  5013.1 2239.51  5021.2 2240.47
  5031.3 2244.57  5041.4 2253.17  5051.5 2262.57  5061.6 2269.29  5066.8 2281.75
  5071.9 2286.31  5081.8 2289.84  5112.2 2296.08  5121.1 2298.49  5125.6 2298.57
#Mann=4,-1,0
  4850.6    0.16       0  5009.1    0.07       0  5013.1    0.16       0
  5121.1   0.035       0
Bank Sta=5009.1,5013.1
Exp/Cntr=0.3,0.1

Type RM Length L Ch R = 1,305,80,80,80
BEGIN DESCRIPTION:
Elm 53 5223
END DESCRIPTION:
XS GIS Cut Line= 3
      1511834.07      6764620.34      1511972.65      6764718.79
      1512101.12      6764737.34
#Sta/Elev= 30
  4830.0 2266.87  4832.3 2266.87  4835.9 2265.84  4850.7 2259.30  4865.5 2255.38
  4871.6 2252.78  4886.4 2251.23  4901.1 2247.51  4907.3 2245.25  4922.0 2243.80
  4936.8 2243.80  4951.6 2243.26  4957.7 2242.09  4978.6 2241.36  5003.7 2241.40
  5012.5 2240.82  5031.6 2238.47  5031.8 2237.97  5035.3 2237.97  5035.6 2238.47
  5042.8 2246.24  5052.9 2255.94  5063.0 2267.29  5073.1 2276.81  5083.2 2281.99
  5093.3 2285.09  5098.9 2288.07  5104.0 2288.51  5123.6 2291.89  5129.8 2293.91
#Mann=3,-1,0
  4830.0    0.16       0  5031.6    0.07       0  5035.6    0.16       0
Bank Sta=5031.6,5035.6
Exp/Cntr=0.3,0.1

Type RM Length L Ch R = 1,225,56,56,56
BEGIN DESCRIPTION:
Elm 53 5222
END DESCRIPTION:
XS GIS Cut Line= 3
      1511810.57      6764658.06      1511918.38      6764764.03
      1512097.08      6764767.45
#Sta/Elev= 30
  4873.3 2264.82  4876.8 2264.82  4897.6 2254.61  4911.7 2248.94  4918.9 2247.37
  4925.9 2244.59  4933.0 2244.47  4940.0 2243.35  4975.4 2240.68  4982.4 2239.52
  4989.6 2239.41  4996.6 2237.52  5008.7 2236.30  5009.0 2235.80  5012.5 2235.80
  5012.7 2236.30  5017.9 2236.81  5023.7 2240.60  5031.1 2243.29  5051.1 2248.56
  5061.1 2250.15  5081.1 2255.74  5091.1 2257.66  5101.1 2261.86  5111.1 2266.99
  5121.1 2269.26  5161.1 2282.02  5181.1 2287.44  5199.6 2291.28  5203.2 2291.28
#Mann=3,-1,0
  4873.3    0.16       0  5008.7    0.07       0  5012.7    0.16       0
Bank Sta=5008.7,5012.7
Exp/Cntr=0.3,0.1

Type RM Length L Ch R = 1,169,102,102,102
BEGIN DESCRIPTION:
Elm 53 5221
END DESCRIPTION:
XS GIS Cut Line= 3
      1511758.54      6764691.95      1511857.18      6764781.91
      1512070.52      6764798.66
#Sta/Elev= 30
  4866.5 2285.13  4875.2 2280.69  4903.4 2260.92  4910.8 2254.28  4925.0 2245.52
  4931.8 2243.43  4939.2 2242.15  4953.4 2240.93  4967.6 2238.29  4974.3 2235.94
  4979.8 2234.99  4980.0 2234.49  4983.5 2234.49  4983.8 2234.99  5007.8 2236.11
  5018.4 2238.43  5027.9 2239.30  5048.0 2249.19  5058.0 2252.83  5068.0 2254.99
  5078.1 2255.87  5098.1 2260.14  5118.2 2263.34  5137.5 2265.79  5142.5 2265.68
  5158.3 2269.46  5178.4 2275.92  5198.4 2281.59  5208.5 2283.81  5214.0 2287.25
#Mann=3,-1,0
  4866.5    0.16       0  4979.8    0.07       0  4983.8    0.16       0
Bank Sta=4979.8,4983.8
Exp/Cntr=0.3,0.1

Type RM Length L Ch R = 1,67,0,0,0
BEGIN DESCRIPTION:
Elm 53 5220
END DESCRIPTION:
XS GIS Cut Line= 3
      1511716.83      6764741.39      1511768.27      6764824.22
      1512020.10      6764829.94
#Sta/Elev= 30
  4902.5 2288.52  4906.5 2287.94  4921.8 2283.46  4933.8 2273.19  4943.1 2268.13
  4948.9 2261.19  4964.3 2250.99  4970.2 2244.55  4979.7 2239.23  4985.6 2235.29
  4990.7 2232.92  4990.9 2232.42  4994.4 2232.42  4994.7 2232.92  5016.7 2237.08
  5046.7 2240.39  5066.8 2240.41  5076.8 2239.42  5096.8 2238.65  5116.8 2241.18
  5136.8 2246.17  5146.8 2249.46  5166.8 2253.90  5176.8 2257.29  5186.8 2259.82
  5216.8 2263.21  5226.8 2263.53  5236.8 2264.82  5246.8 2267.56  5251.9 2270.17
#Mann=3,-1,0
  4902.5    0.16       0  4990.7    0.07       0  4994.7    0.16       0
Bank Sta=4990.7,4994.7
Exp/Cntr=0.3,0.1

Chan Stop Cuts=-1