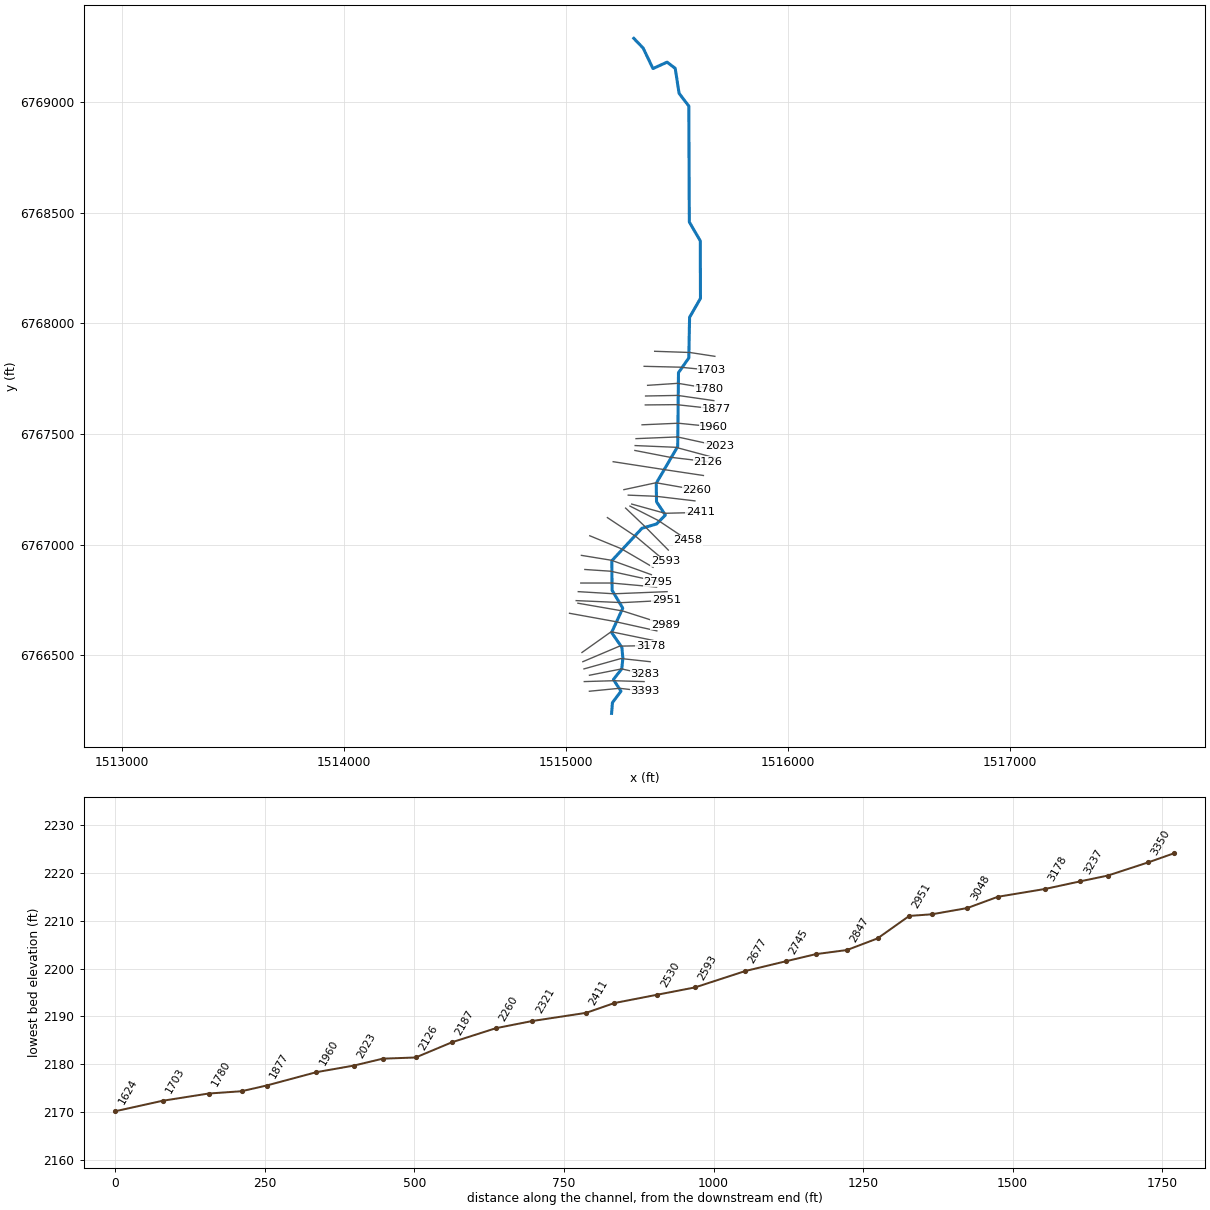
--- Elm 54.prj (project) ---

Proj Title=Elm 54 Base Level Engineering
Current Plan=p01
Default Exp/Contr=0.3,0.1
English Units
Geom File=g01
Flow File=f01
Plan File=p01
BEGIN DESCRIPTION:
Elm 54
END DESCRIPTION:

--- Elm 54.p01 (plan) ---

Plan Title=Multiple Run
Short Identifier=Multiple
Geom File=g01
Flow File=f01
Subcritical Flow
K Sum by GR= 0
Std Step Tol= 0.01
Critical Tol= 0.01
Num of Std Step Trials= 20
Max Error Tol= 0.3
Flow Tol Ratio= 0.001
Split Flow NTrial= 30
Split Flow Tol= 0.02
Split Flow Ratio= 0.02
Log Output Level= 0
Friction Slope Method= 1
Unsteady Friction Slope Method= 2
Unsteady Bridges Friction Slope Method= 1
Parabolic Critical Depth
Global Vel Dist=  1 , 1 , 1
Global Log Level= 0
CheckData=True
Encroach Param= -1, 0, 0, 0
BEGIN DESCRIPTION:
Multiple Run
END DESCRIPTION:

--- Elm 54.f01 (steady flow) ---

Flow Title=Multiple
Number of Profiles=7
Profile Names=10-year,25-year,50-year,1pct_min,100-year,1pct_plu,500-year
River Rch & RM= Elm 54,Reach-1,3393
     224     314     391     303     485     668     757
Boundary for River Rch & Prof#=Elm 54,Reach-1,1
Up Type=0
Dn Type=3
Dn Slope=0.005
Boundary for River Rch & Prof#=Elm 54,Reach-1,2
Up Type=0
Dn Type=3
Dn Slope=0.005
Boundary for River Rch & Prof#=Elm 54,Reach-1,3
Up Type=0
Dn Type=3
Dn Slope=0.005
Boundary for River Rch & Prof#=Elm 54,Reach-1,4
Up Type=0
Dn Type=3
Dn Slope=0.005
Boundary for River Rch & Prof#=Elm 54,Reach-1,5
Up Type=0
Dn Type=3
Dn Slope=0.005
Boundary for River Rch & Prof#=Elm 54,Reach-1,6
Up Type=0
Dn Type=3
Dn Slope=0.005
Boundary for River Rch & Prof#=Elm 54,Reach-1,7
Up Type=0
Dn Type=3
Dn Slope=0.005

--- Elm 54.g01 (geometry) ---

Geom Title=Existing Conditions

River Reach=Elm 54,Reach-1
Reach XY= 30
      1515205.00      6766238.00      1515208.98      6766286.64
      1515247.43      6766338.06      1515213.27      6766391.22
      1515251.07      6766439.50      1515255.78      6766487.99
      1515251.26      6766536.41      1515205.10      6766603.40
      1515255.39      6766713.00      1515207.28      6766793.93
      1515206.04      6766927.56      1515341.82      6767074.37
      1515407.85      6767093.85      1515447.31      6767134.33
      1515407.38      6767193.88      1515406.09      6767277.45
      1515502.76      6767443.93      1515506.22      6767777.50
      1515552.74      6767843.94      1515556.22      6768027.49
      1515605.20      6768112.92      1515604.48      6768372.78
      1515555.07      6768458.03      1515552.74      6768982.06
      1515508.86      6769039.60      1515491.60      6769152.09
      1515455.23      6769180.54      1515391.32      6769151.47
      1515347.06      6769244.08      1515305.00      6769288.00

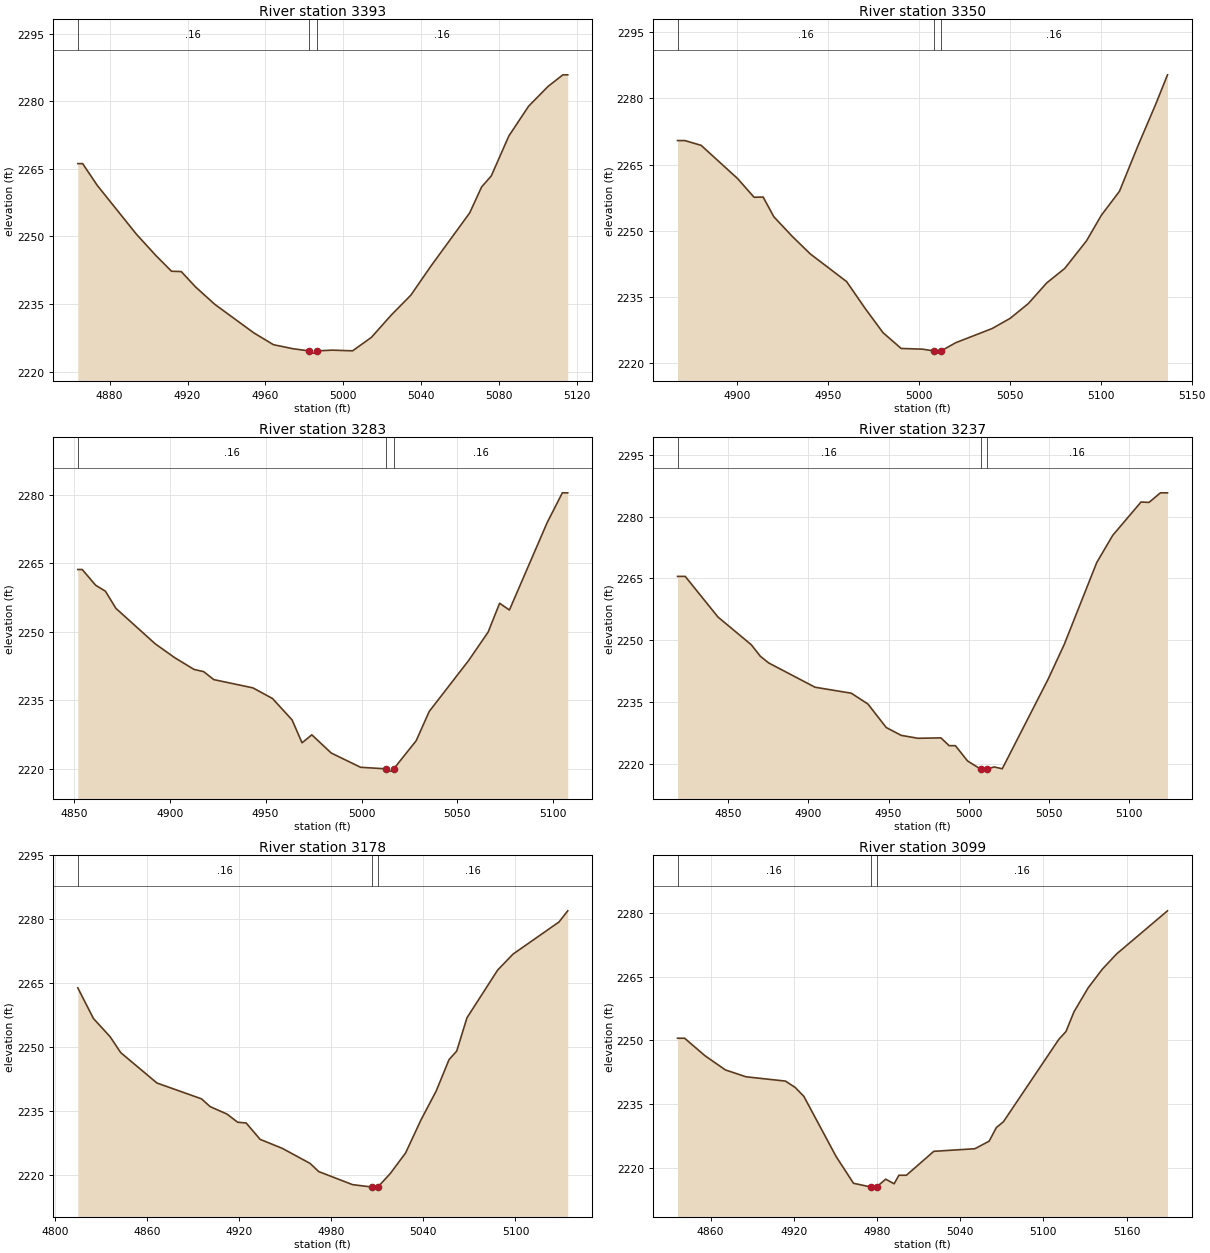
Type RM Length L Ch R = 1,3393,43,43,43
BEGIN DESCRIPTION:
elmc384
END DESCRIPTION:
XS GIS Cut Line= 3
      1515105.03      6766338.00      1515240.68      6766351.35
      1515355.00      6766338.00
#Sta/Elev= 30
  4863.7 2266.15  4866.2 2266.15  4873.7 2261.32  4893.8 2250.49  4903.9 2245.71
  4911.8 2242.29  4916.8 2242.21  4924.0 2238.86  4934.0 2234.95  4954.1 2228.60
  4964.1 2226.00  4974.2 2225.10  4982.2 2224.63  4982.5 2224.13  4986.0 2224.13
  4986.2 2224.63  4994.3 2224.79  5004.7 2224.64  5014.4 2227.64  5024.5 2232.55
  5034.6 2236.98  5044.6 2243.25  5064.8 2255.23  5070.9 2260.97  5075.9 2263.45
  5084.9 2272.29  5095.0 2278.87  5105.0 2283.27  5112.6 2285.84  5115.1 2285.84
#Mann=3,-1,0
  4863.7    0.16       0  4982.2    0.07       0  4986.2    0.16       0
Bank Sta=4982.2,4986.2
Exp/Cntr=0.3,0.1

Type RM Length L Ch R = 1,3350,67,67,67
BEGIN DESCRIPTION:
elmc448
END DESCRIPTION:
XS GIS Cut Line= 3
      1515082.04      6766381.63      1515213.56      6766385.53
      1515351.43      6766381.67
#Sta/Elev= 30
  4867.2 2270.45  4871.2 2270.45  4880.2 2269.36  4900.2 2261.84  4909.3 2257.59
  4914.3 2257.63  4920.2 2253.15  4930.2 2248.76  4940.2 2244.74  4960.2 2238.46
  4970.2 2232.49  4980.2 2226.88  4990.2 2223.29  5002.0 2223.13  5008.2 2222.73
  5008.5 2222.23  5012.0 2222.23  5012.2 2222.73  5020.2 2224.59  5040.2 2227.80
  5050.2 2230.13  5060.2 2233.49  5070.2 2238.13  5080.2 2241.45  5092.2 2247.73
  5100.3 2253.49  5110.3 2258.95  5120.3 2269.11  5130.3 2278.77  5136.7 2285.36
#Mann=3,-1,0
  4867.2    0.16       0  5008.2    0.07       0  5012.2    0.16       0
Bank Sta=5008.2,5012.2
Exp/Cntr=0.3,0.1

Type RM Length L Ch R = 1,3283,46,46,46
BEGIN DESCRIPTION:
elmc447
END DESCRIPTION:
XS GIS Cut Line= 3
      1515105.46      6766410.27      1515250.01      6766438.92
      1515355.47      6766415.48
#Sta/Elev= 30
  4852.1 2263.64  4854.4 2263.64  4861.4 2260.20  4866.5 2258.89  4872.0 2255.12
  4892.4 2247.39  4902.6 2244.34  4912.7 2241.76  4917.7 2241.28  4923.0 2239.53
  4943.4 2237.72  4953.6 2235.39  4963.8 2230.71  4969.0 2225.69  4974.1 2227.44
  4984.2 2223.46  4999.5 2220.33  5012.8 2219.99  5013.1 2219.49  5016.6 2219.49
  5016.8 2219.99  5028.5 2226.15  5035.3 2232.56  5055.8 2243.69  5066.0 2249.93
  5072.0 2256.25  5077.1 2254.77  5096.8 2273.93  5104.7 2280.43  5107.5 2280.43
#Mann=3,-1,0
  4852.1    0.16       0  5012.8    0.07       0  5016.8    0.16       0
Bank Sta=5012.8,5016.8
Exp/Cntr=0.3,0.1

Type RM Length L Ch R = 1,3237,59,59,59
BEGIN DESCRIPTION:
elmc446
END DESCRIPTION:
XS GIS Cut Line= 3
      1515080.72      6766438.91      1515247.41      6766485.79
      1515378.87      6766471.47
#Sta/Elev= 30
  4818.5 2265.48  4823.3 2265.48  4843.7 2255.64  4864.5 2248.90  4870.1 2246.13
  4875.3 2244.51  4904.2 2238.62  4926.8 2237.17  4937.2 2234.54  4948.6 2228.85
  4958.0 2226.94  4968.4 2226.24  4982.7 2226.34  4987.8 2224.45  4991.7 2224.45
  4999.3 2220.74  5007.4 2218.78  5007.6 2218.28  5011.1 2218.28  5011.4 2218.78
  5015.9 2219.30  5020.9 2218.85  5049.6 2240.65  5059.6 2249.04  5079.8 2268.84
  5089.8 2275.45  5107.4 2283.51  5112.4 2283.42  5119.5 2285.74  5123.9 2285.74
#Mann=3,-1,0
  4818.5    0.16       0  5007.4    0.07       0  5011.4    0.16       0
Bank Sta=5007.4,5011.4
Exp/Cntr=0.3,0.1

Type RM Length L Ch R = 1,3178,79,79,79
BEGIN DESCRIPTION:
elmc445
END DESCRIPTION:
XS GIS Cut Line= 3
      1515075.58      6766471.49      1515240.90      6766541.78
      1515380.73      6766544.37
#Sta/Elev= 30
  4814.6 2263.91  4824.8 2256.72  4835.7 2252.43  4842.6 2248.71  4866.2 2241.58
  4895.3 2237.86  4900.9 2236.04  4911.8 2234.31  4918.9 2232.37  4924.4 2232.20
  4933.5 2228.36  4948.0 2226.24  4966.1 2222.71  4971.7 2220.80  4993.8 2217.73
  5006.3 2217.18  5006.6 2216.68  5010.1 2216.68  5010.3 2217.18  5018.4 2220.35
  5028.4 2225.19  5038.4 2232.92  5048.4 2239.76  5056.7 2247.07  5061.7 2249.07
  5068.4 2256.89  5088.4 2268.08  5098.4 2271.82  5128.4 2279.36  5134.1 2281.98
#Mann=3,-1,0
  4814.6    0.16       0  5006.3    0.07       0  5010.3    0.16       0
Bank Sta=5006.3,5010.3
Exp/Cntr=0.3,0.1

Type RM Length L Ch R = 1,3099,51,51,51
BEGIN DESCRIPTION:
elmc444
END DESCRIPTION:
XS GIS Cut Line= 3
      1515071.64      6766513.15      1515203.14      6766606.89
      1515390.97      6766568.02
#Sta/Elev= 30
  4836.2 2250.53  4841.3 2250.53  4856.0 2246.41  4870.7 2243.08  4885.5 2241.46
  4914.0 2240.45  4921.1 2238.94  4927.3 2236.85  4950.6 2222.68  4963.1 2216.41
  4975.7 2215.54  4975.9 2215.04  4979.4 2215.04  4979.7 2215.54  4986.3 2217.38
  4992.4 2216.30  4995.8 2218.30  5001.2 2218.30  5021.0 2223.93  5050.6 2224.54
  5060.9 2226.32  5066.1 2229.52  5071.2 2230.89  5111.2 2250.29  5116.3 2252.10
  5122.1 2256.76  5132.3 2262.38  5142.6 2266.80  5152.8 2270.35  5189.5 2280.49
#Mann=3,-1,0
  4836.2    0.16       0  4975.7    0.07       0  4979.7    0.16       0
Bank Sta=4975.7,4979.7
Exp/Cntr=0.3,0.1

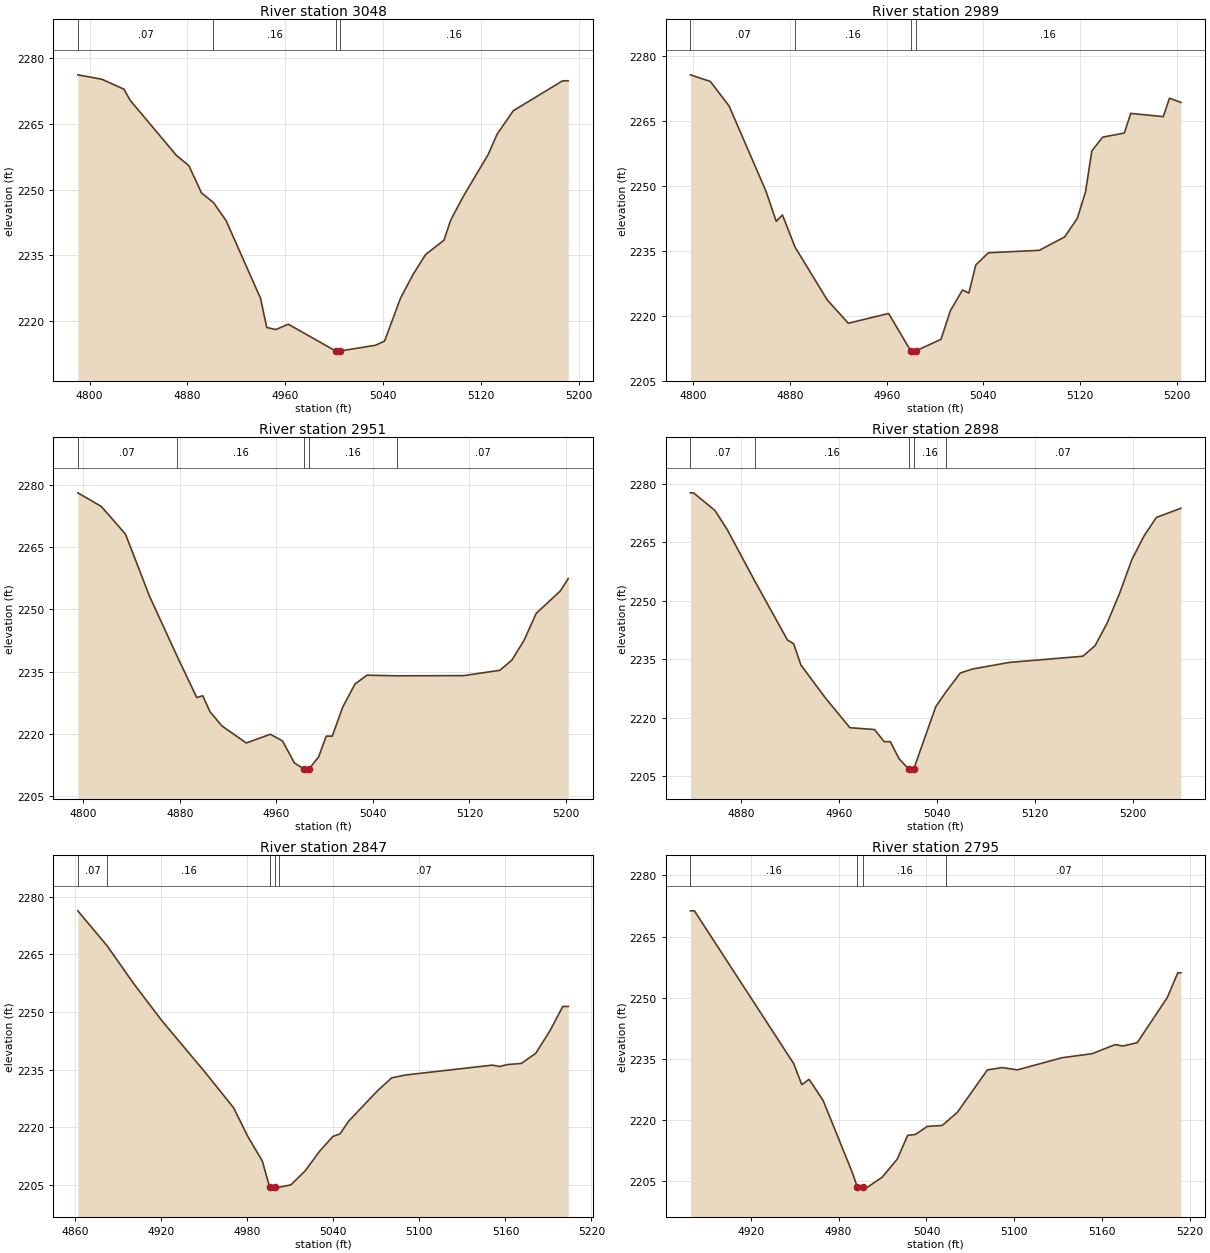
Type RM Length L Ch R = 1,3048,59,59,59
BEGIN DESCRIPTION:
elmc443
END DESCRIPTION:
XS GIS Cut Line= 3
      1515015.61      6766690.23      1515216.16      6766653.76
      1515408.89      6766610.79
#Sta/Elev= 30
  4790.3 2276.17  4810.0 2275.16  4828.0 2272.91  4833.1 2270.37  4871.0 2257.79
  4881.2 2255.44  4891.5 2249.23  4901.3 2247.03  4911.6 2242.93  4939.8 2225.19
  4944.9 2218.53  4952.3 2218.06  4962.5 2219.28  5001.2 2213.18  5001.4 2212.68
  5004.9 2212.68  5005.2 2213.18  5033.9 2214.48  5041.3 2215.42  5054.4 2225.25
  5064.7 2230.66  5074.9 2235.18  5089.9 2238.44  5095.4 2243.02  5105.7 2248.43
  5126.1 2258.00  5133.4 2262.64  5146.6 2267.97  5187.0 2274.81  5191.6 2274.81
#Mann=4,-1,0
  4790.3    0.07       0  4901.3    0.16       0  5001.2    0.07       0
  5005.2    0.16       0
Bank Sta=5001.2,5005.2
Exp/Cntr=0.3,0.1

Type RM Length L Ch R = 1,2989,38,38,38
BEGIN DESCRIPTION:
elmc442
END DESCRIPTION:
XS GIS Cut Line= 3
      1515053.44      6766735.78      1515255.22      6766700.64
      1515446.66      6766639.43
#Sta/Elev= 30
  4797.6 2275.61  4814.1 2274.07  4829.6 2268.41  4860.1 2248.75  4868.6 2241.79
  4873.7 2243.28  4884.1 2235.87  4910.8 2223.65  4928.2 2218.28  4961.6 2220.53
  4979.9 2211.88  4980.1 2211.38  4983.9 2211.88  5004.9 2214.56  5012.7 2221.19
  5022.7 2225.94  5028.0 2225.26  5033.7 2231.74  5044.2 2234.55  5086.2 2235.10
  5107.2 2238.19  5117.7 2242.48  5124.5 2248.61  5129.7 2258.04  5138.7 2261.23
  5156.6 2262.17  5161.9 2266.71  5188.8 2265.96  5194.0 2270.23  5203.4 2269.24
#Mann=4,-1,0
  4797.6    0.07       0  4884.1    0.16       0  4979.9    0.07       0
  4983.9    0.16       0
Bank Sta=4979.9,4983.9
Exp/Cntr=0.3,0.1

Type RM Length L Ch R = 1,2951,53,53,53
BEGIN DESCRIPTION:
elmc441
END DESCRIPTION:
XS GIS Cut Line= 3
      1515045.57      6766747.51      1515252.62      6766738.40
      1515451.60      6766748.73
#Sta/Elev= 30
  4795.4 2278.07  4814.8 2274.81  4834.9 2268.13  4854.9 2253.12  4877.4 2238.89
  4894.0 2228.75  4899.0 2229.19  4904.9 2225.35  4914.9 2221.91  4935.0 2217.81
  4955.0 2219.91  4965.0 2218.32  4975.0 2212.98  4983.0 2211.53  4983.3 2211.03
  4987.0 2211.53  4995.0 2214.46  5001.3 2219.46  5006.3 2219.46  5015.0 2226.47
  5025.1 2232.00  5035.1 2234.14  5059.9 2233.99  5115.2 2234.04  5145.2 2235.32
  5155.2 2237.79  5165.2 2242.50  5175.3 2249.02  5195.3 2254.42  5201.9 2257.42
#Mann=5,-1,0
  4795.4    0.07       0  4877.4    0.16       0  4983.0    0.07       0
  4987.0    0.16       0  5059.9    0.07       0
Bank Sta=4983,4987
Exp/Cntr=0.3,0.1

Type RM Length L Ch R = 1,2898,51,51,51
BEGIN DESCRIPTION:
elmc383
END DESCRIPTION:
XS GIS Cut Line= 3
      1515055.00      6766788.00      1515215.91      6766778.33
      1515455.01      6766788.00
#Sta/Elev= 30
  4838.8 2277.70  4841.3 2277.70  4858.8 2273.18  4868.9 2268.23  4891.4 2255.05
  4918.0 2239.95  4923.1 2238.98  4929.0 2233.54  4949.0 2225.09  4969.0 2217.46
  4989.1 2216.99  4997.0 2213.88  5002.0 2213.88  5009.1 2209.53  5017.1 2206.82
  5017.4 2206.32  5021.1 2206.82  5039.1 2222.82  5047.1 2226.48  5059.1 2231.47
  5069.1 2232.51  5099.2 2234.20  5159.2 2235.79  5169.2 2238.48  5179.2 2244.36
  5189.2 2251.89  5199.3 2260.60  5209.3 2266.69  5219.3 2271.39  5239.3 2273.74
#Mann=5,-1,0
  4838.8    0.07       0  4891.4    0.16       0  5017.1    0.07       0
  5021.1    0.16       0  5047.1    0.07       0
Bank Sta=5017.1,5021.1
Exp/Cntr=0.3,0.1

Type RM Length L Ch R = 1,2847,52,52,52
BEGIN DESCRIPTION:
elmc440
END DESCRIPTION:
XS GIS Cut Line= 3
      1515066.39      6766826.94      1515204.44      6766826.94
      1515407.58      6766808.71
#Sta/Elev= 30
  4861.8 2276.31  4882.4 2267.13  4900.4 2257.55  4920.4 2247.73  4950.4 2234.37
  4970.4 2225.08  4980.4 2217.56  4990.4 2211.26  4995.6 2204.39  4995.9 2203.89
  4999.4 2203.89  4999.6 2204.39  5002.4 2204.39  5010.4 2205.01  5020.5 2208.71
  5030.5 2213.80  5039.7 2217.61  5044.7 2218.27  5050.6 2221.55  5070.7 2229.45
  5080.7 2232.86  5090.8 2233.61  5150.9 2236.16  5155.9 2235.79  5161.1 2236.29
  5171.1 2236.60  5181.1 2239.22  5191.2 2245.19  5200.0 2251.43  5203.8 2251.43
#Mann=5,-1,0
  4861.8    0.07       0  4882.4    0.16       0  4995.6    0.07       0
  4999.6    0.16       0  5002.4    0.07       0
Bank Sta=4995.6,4999.6
Exp/Cntr=0.3,0.1

Type RM Length L Ch R = 1,2795,50,50,50
BEGIN DESCRIPTION:
elmc439
END DESCRIPTION:
XS GIS Cut Line= 3
      1515084.62      6766888.14      1515200.54      6766880.32
      1515414.07      6766833.45
#Sta/Elev= 30
  4878.9 2271.32  4881.6 2271.32  4949.4 2233.82  4954.9 2228.67  4959.9 2229.98
  4969.5 2224.76  4989.5 2207.02  4992.8 2203.53  4993.1 2203.03  4996.8 2203.53
  4999.9 2203.53  5009.9 2205.99  5020.1 2210.41  5027.2 2216.24  5032.4 2216.43
  5040.6 2218.42  5050.8 2218.66  5053.5 2219.50  5061.1 2221.87  5081.6 2232.28
  5091.8 2232.86  5102.0 2232.29  5132.7 2235.28  5153.2 2236.27  5168.9 2238.51
  5174.0 2238.14  5183.9 2238.96  5204.4 2250.04  5211.6 2256.11  5213.7 2256.11
#Mann=4,-1,0
  4878.9    0.16       0  4992.8    0.07       0  4996.8    0.16       0
  5053.5    0.07       0
Bank Sta=4992.8,4996.8
Exp/Cntr=0.3,0.1

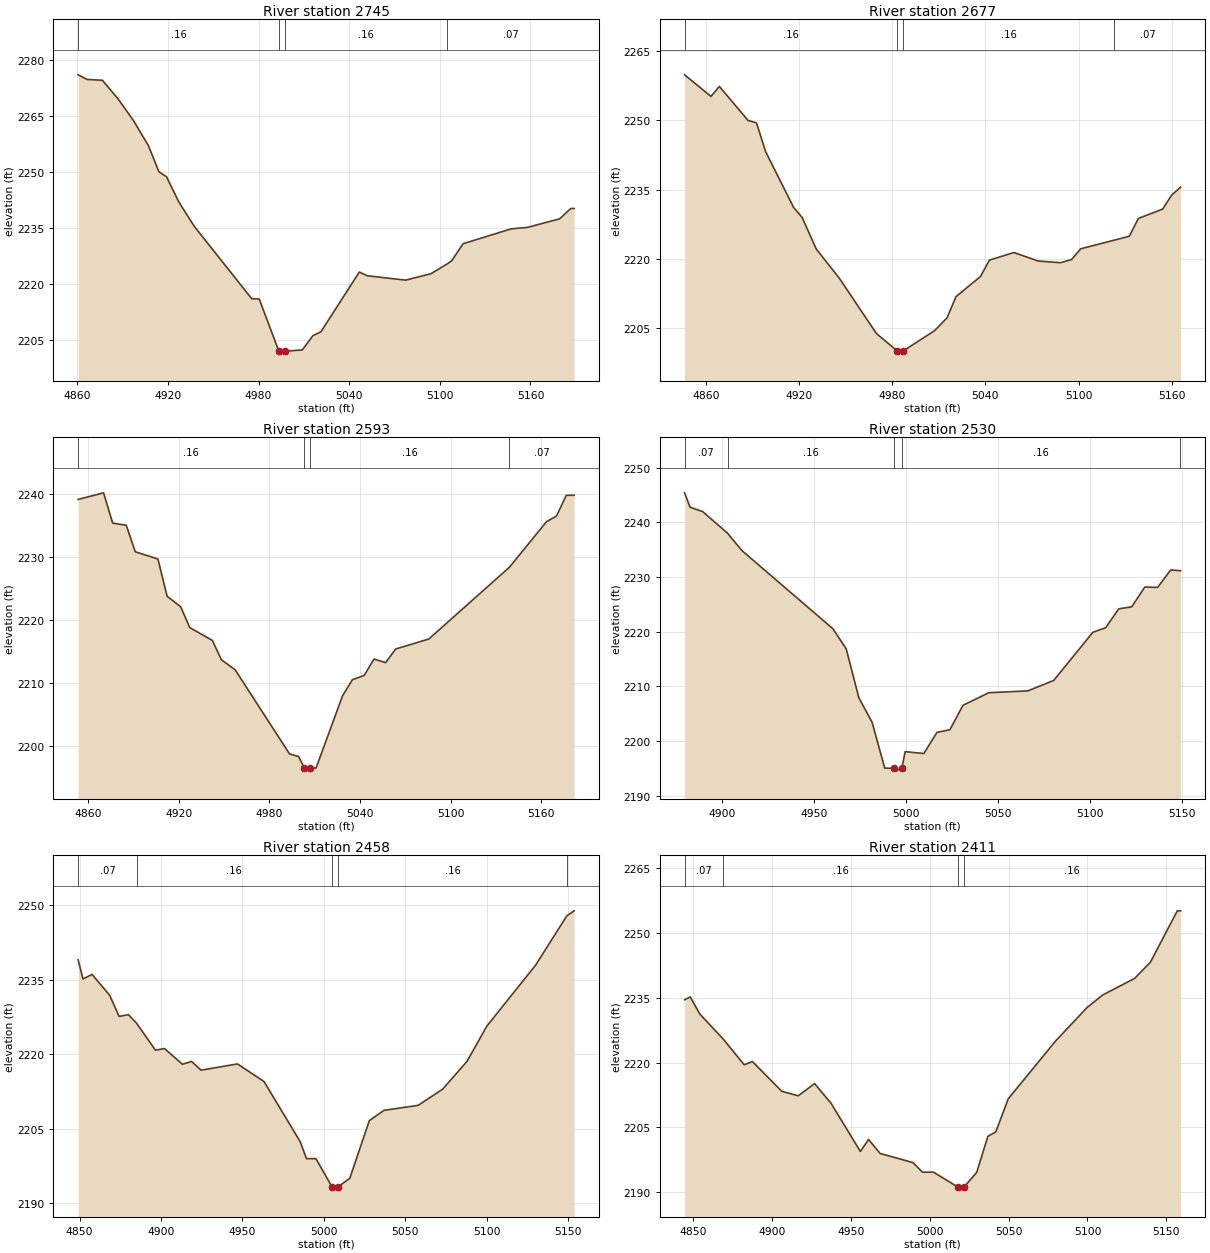
Type RM Length L Ch R = 1,2745,68,68,68
BEGIN DESCRIPTION:
elmc438
END DESCRIPTION:
XS GIS Cut Line= 3
      1515069.07      6766951.93      1515204.44      6766929.80
      1515384.14      6766864.69
#Sta/Elev= 30
  4860.6 2276.02  4866.6 2274.78  4876.7 2274.56  4886.9 2269.67  4897.0 2263.93
  4907.1 2257.11  4914.1 2250.08  4919.1 2248.76  4927.4 2241.90  4937.5 2235.47
  4975.5 2216.11  4980.5 2216.01  4993.5 2202.04  4993.8 2201.54  4997.5 2202.04
  5009.0 2202.40  5016.0 2206.21  5021.3 2207.24  5046.7 2223.23  5052.0 2222.25
  5077.3 2221.07  5094.1 2222.79  5104.9 2225.42  5107.9 2226.26  5115.4 2230.82
  5147.3 2234.80  5157.9 2235.19  5179.2 2237.46  5186.7 2240.25  5188.9 2240.25
#Mann=4,-1,0
  4860.6    0.16       0  4993.5    0.07       0  4997.5    0.16       0
  5104.9    0.07       0
Bank Sta=4993.5,4997.5
Exp/Cntr=0.3,0.1

Type RM Length L Ch R = 1,2677,84,84,84
BEGIN DESCRIPTION:
elmc437
END DESCRIPTION:
XS GIS Cut Line= 3
      1515106.74      6767040.50      1515248.71      6766981.89
      1515391.62      6766898.20
#Sta/Elev= 30
  4846.4 2259.89  4863.4 2255.20  4868.8 2257.37  4887.3 2249.98  4892.7 2249.46
  4898.6 2243.19  4916.6 2231.10  4922.1 2228.93  4931.1 2222.10  4946.0 2215.75
  4969.9 2203.73  4983.2 2199.99  4983.4 2199.49  4987.2 2199.99  5007.3 2204.37
  5015.3 2207.15  5021.1 2211.76  5036.8 2216.11  5042.6 2219.68  5058.3 2221.32
  5074.0 2219.48  5088.4 2219.11  5095.5 2219.81  5101.3 2222.13  5122.8 2224.00
  5132.6 2224.86  5138.4 2228.72  5154.1 2230.76  5159.9 2233.82  5165.6 2235.51
#Mann=4,-1,0
  4846.4    0.16       0  4983.2    0.07       0  4987.2    0.16       0
  5122.8    0.07       0
Bank Sta=4983.2,4987.2
Exp/Cntr=0.3,0.1

Type RM Length L Ch R = 1,2593,63,63,63
BEGIN DESCRIPTION:
elmc436
END DESCRIPTION:
XS GIS Cut Line= 3
      1515186.18      6767122.53      1515315.12      6767036.57
      1515447.95      6766924.58
#Sta/Elev= 30
  4853.2 2239.21  4870.1 2240.26  4876.1 2235.45  4885.1 2235.11  4891.1 2230.90
  4906.1 2229.75  4912.2 2223.83  4921.2 2222.16  4927.2 2218.86  4942.2 2216.81
  4948.2 2213.73  4957.2 2212.18  4993.3 2198.80  4999.3 2198.38  5003.1 2196.56
  5003.3 2196.06  5007.1 2196.56  5010.9 2196.56  5028.4 2208.00  5035.0 2210.59
  5042.7 2211.24  5049.3 2213.86  5057.0 2213.29  5063.6 2215.45  5085.6 2217.04
  5139.0 2228.44  5163.6 2235.68  5170.2 2236.57  5176.7 2239.87  5181.9 2239.87
#Mann=4,-1,0
  4853.2    0.16       0  5003.1    0.07       0  5007.1    0.16       0
  5139.0    0.07       0
Bank Sta=5003.1,5007.1
Exp/Cntr=0.3,0.1

Type RM Length L Ch R = 1,2530,72,72,72
BEGIN DESCRIPTION:
elmc435
END DESCRIPTION:
XS GIS Cut Line= 3
      1515268.23      6767165.50      1515355.48      6767082.15
      1515460.50      6766975.84
#Sta/Elev= 30
  4879.4 2245.38  4882.4 2242.75  4889.3 2241.95  4902.8 2238.00  4910.7 2234.81
  4960.1 2220.57  4967.4 2216.89  4974.3 2207.94  4981.5 2203.47  4988.4 2195.08
  4993.7 2195.03  4993.9 2194.53  4997.7 2195.03  4999.5 2198.09  5009.7 2197.75
  5016.8 2201.59  5023.9 2202.11  5031.0 2206.56  5045.1 2208.86  5066.3 2209.19
  5080.4 2211.10  5101.7 2219.89  5108.7 2220.74  5115.8 2224.18  5122.9 2224.55
  5130.0 2228.17  5137.0 2228.10  5144.1 2231.29  5148.9 2231.16  5149.5 2231.14
#Mann=5,-1,0
  4879.4    0.07       0  4902.8    0.16       0  4993.7    0.07       0
  4997.7    0.16       0  5148.9    0.07       0
Bank Sta=4993.7,4997.7
Exp/Cntr=0.3,0.1

Type RM Length L Ch R = 1,2458,47,47,47
BEGIN DESCRIPTION:
elmc434
END DESCRIPTION:
XS GIS Cut Line= 3
      1515287.76      6767174.60      1515415.38      6767109.49
      1515549.50      6767019.65
#Sta/Elev= 30
  4849.1 2239.04  4852.1 2235.18  4857.7 2236.08  4868.5 2231.88  4874.3 2227.61
  4880.0 2227.98  4885.1 2226.22  4896.6 2220.81  4902.2 2221.13  4913.2 2217.96
  4918.8 2218.54  4924.6 2216.77  4947.0 2218.03  4963.3 2214.49  4985.5 2202.36
  4989.4 2198.93  4995.2 2198.93  5005.0 2193.28  5005.3 2192.78  5009.0 2193.28
  5016.0 2194.98  5028.0 2206.60  5037.0 2208.67  5058.0 2209.68  5073.0 2212.93
  5088.0 2218.55  5100.2 2225.67  5130.1 2237.94  5149.3 2247.90  5153.8 2248.91
#Mann=5,-1,0
  4849.1    0.07       0  4885.1    0.16       0  5005.0    0.07       0
  5009.0    0.16       0  5149.3    0.07       0
Bank Sta=5005,5009
Exp/Cntr=0.3,0.1

Type RM Length L Ch R = 1,2411,90,90,90
BEGIN DESCRIPTION:
elmc433
END DESCRIPTION:
XS GIS Cut Line= 3
      1515295.62      6767183.70      1515445.33      6767142.04
      1515604.18      6767145.95
#Sta/Elev= 30
  4844.7 2234.51  4848.3 2235.18  4854.4 2231.20  4869.3 2225.39  4882.5 2219.48
  4887.7 2220.23  4906.3 2213.35  4916.7 2212.31  4927.1 2215.13  4937.5 2210.59
  4956.1 2199.44  4961.3 2202.21  4968.6 2198.98  4989.4 2196.87  4995.5 2194.64
  5002.4 2194.66  5017.8 2191.23  5018.0 2190.73  5021.8 2191.23  5029.8 2194.60
  5036.9 2202.94  5041.9 2203.97  5049.8 2211.62  5079.8 2224.99  5099.8 2232.74
  5109.8 2235.66  5129.8 2239.44  5139.8 2243.16  5156.9 2255.08  5159.0 2255.08
#Mann=4,-1,0
  4844.7    0.07       0  4869.3    0.16       0  5017.8    0.07       0
  5021.8    0.16       0
Bank Sta=5017.8,5021.8
Exp/Cntr=0.3,0.1

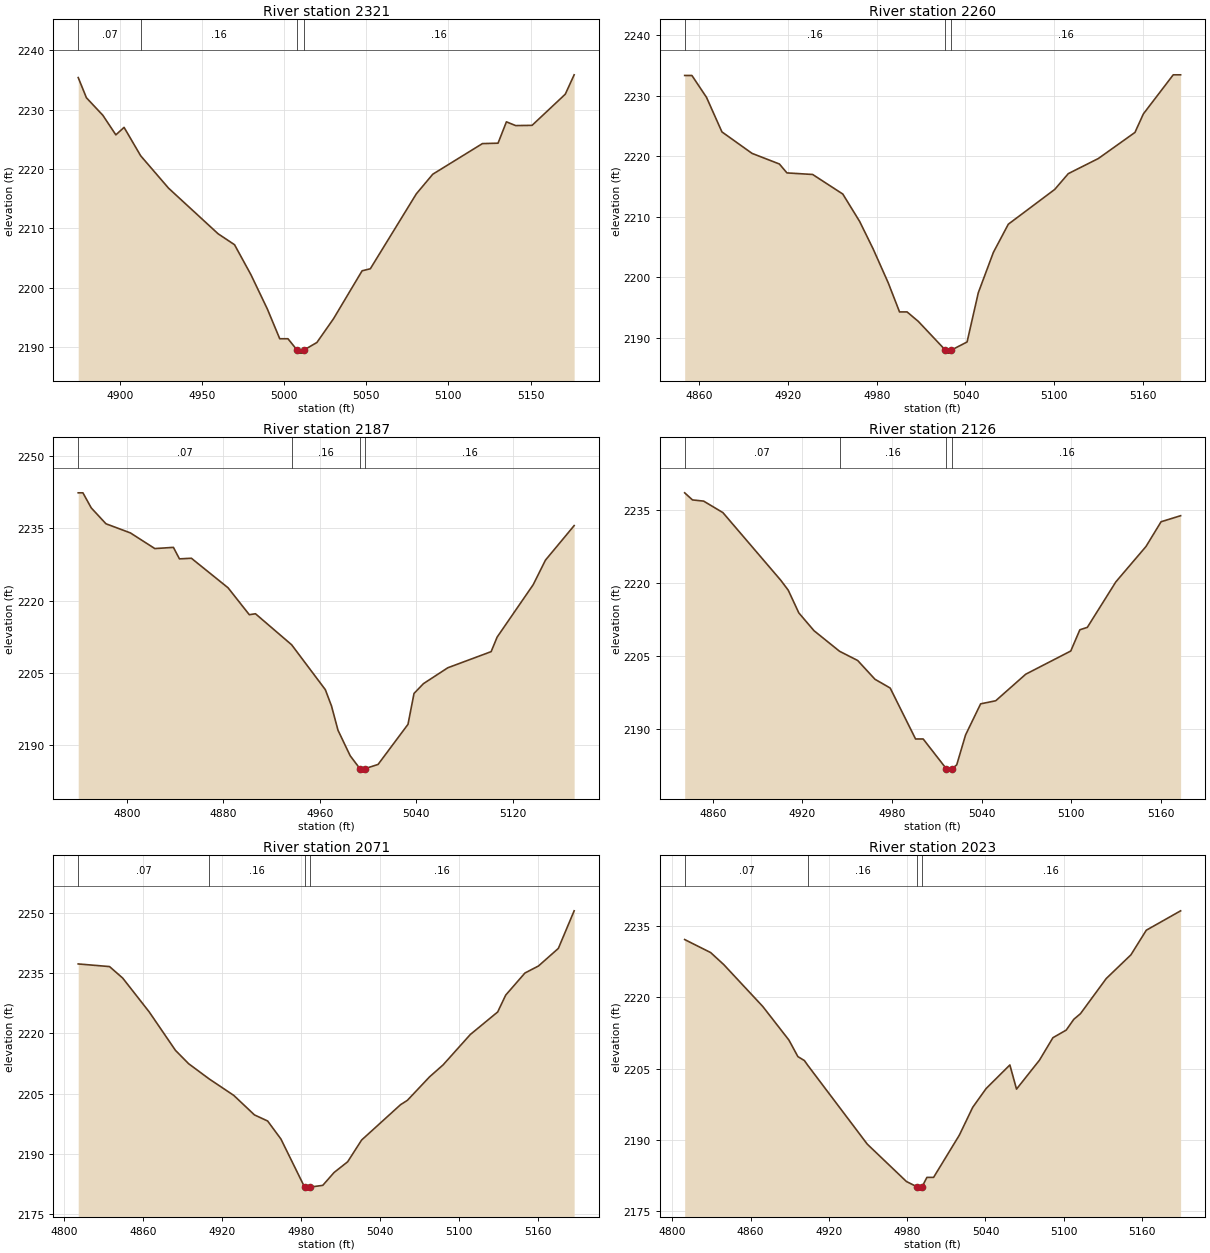
Type RM Length L Ch R = 1,2321,61,61,61
BEGIN DESCRIPTION:
elmc432
END DESCRIPTION:
XS GIS Cut Line= 3
      1515280.01      6767224.07      1515404.96      6767218.87
      1515580.37      6767198.08
#Sta/Elev= 30
  4874.8 2235.38  4879.8 2231.98  4889.8 2229.03  4897.7 2225.74  4902.7 2227.00
  4912.8 2222.22  4929.8 2216.76  4959.9 2209.10  4969.9 2207.26  4979.9 2202.20
  4989.9 2196.42  4997.4 2191.44  5002.4 2191.44  5008.0 2189.52  5008.2 2189.02
  5011.7 2189.02  5012.0 2189.52  5020.0 2190.81  5030.1 2194.80  5047.5 2202.87
  5052.5 2203.21  5080.5 2215.82  5090.5 2219.12  5120.7 2224.27  5130.2 2224.34
  5135.3 2227.93  5140.9 2227.30  5150.9 2227.34  5171.1 2232.58  5176.5 2235.84
#Mann=4,-1,0
  4874.8    0.07       0  4912.8    0.16       0  5008.0    0.07       0
  5012.0    0.16       0
Bank Sta=5008,5012
Exp/Cntr=0.3,0.1

Type RM Length L Ch R = 1,2260,73,73,73
BEGIN DESCRIPTION:
elmc431
END DESCRIPTION:
XS GIS Cut Line= 3
      1515260.40      6767248.81      1515404.96      6767280.06
      1515589.82      6767247.52
#Sta/Elev= 30
  4850.0 2233.34  4854.9 2233.34  4864.8 2229.72  4875.2 2224.03  4895.6 2220.48
  4914.1 2218.73  4919.2 2217.26  4936.6 2217.00  4957.0 2213.77  4968.4 2209.25
  4977.5 2204.73  4987.7 2199.14  4995.4 2194.31  5000.5 2194.31  5008.1 2192.75
  5026.4 2188.01  5026.6 2187.51  5030.1 2187.51  5030.4 2188.01  5041.1 2189.35
  5048.7 2197.48  5058.9 2204.14  5069.0 2208.79  5100.4 2214.53  5109.6 2217.14
  5129.9 2219.63  5154.7 2223.94  5160.4 2227.00  5180.6 2233.45  5185.6 2233.45
#Mann=3,-1,0
  4850.0    0.16       0  5026.4    0.07       0  5030.4    0.16       0
Bank Sta=5026.4,5030.4
Exp/Cntr=0.3,0.1

Type RM Length L Ch R = 1,2187,61,61,61
BEGIN DESCRIPTION:
elmc430
END DESCRIPTION:
XS GIS Cut Line= 3
      1515212.26      6767375.11      1515455.74      6767337.35
      1515618.51      6767312.81
#Sta/Elev= 30
  4759.8 2242.39  4763.7 2242.39  4770.6 2239.26  4782.8 2235.96  4803.0 2234.07
  4823.3 2230.81  4838.7 2231.06  4843.7 2228.67  4853.6 2228.80  4884.0 2222.66
  4901.6 2217.07  4906.7 2217.27  4936.7 2210.82  4964.6 2201.50  4969.7 2198.12
  4975.1 2193.07  4985.2 2187.77  4993.3 2185.08  4993.6 2184.58  4997.3 2185.08
  5008.3 2185.97  5033.1 2194.30  5038.1 2200.72  5045.9 2202.75  5066.1 2206.05
  5102.0 2209.40  5107.0 2212.43  5136.9 2223.32  5147.0 2228.40  5170.8 2235.58
#Mann=4,-1,0
  4759.8    0.07       0  4936.7    0.16       0  4993.3    0.07       0
  4997.3    0.16       0
Bank Sta=4993.3,4997.3
Exp/Cntr=0.3,0.1

Type RM Length L Ch R = 1,2126,55,55,55
BEGIN DESCRIPTION:
elmc428
END DESCRIPTION:
XS GIS Cut Line= 3
      1515309.89      6767425.90      1515463.56      6767395.95
      1515638.06      6767375.11
#Sta/Elev= 30
  4841.1 2238.42  4846.3 2236.97  4853.8 2236.72  4866.7 2234.37  4905.4 2220.53
  4910.5 2218.46  4917.6 2213.80  4927.8 2210.15  4944.9 2205.94  4957.0 2204.06
  4968.6 2200.21  4978.8 2198.41  4995.8 2187.97  5000.9 2187.97  5016.4 2181.88
  5016.6 2181.38  5020.1 2181.38  5020.4 2181.88  5023.4 2182.68  5029.3 2188.79
  5039.4 2195.17  5049.5 2195.80  5069.6 2201.24  5099.8 2206.00  5105.9 2210.35
  5110.9 2210.85  5130.0 2220.17  5150.2 2227.42  5160.3 2232.49  5173.4 2233.73
#Mann=4,-1,0
  4841.1    0.07       0  4944.9    0.16       0  5016.4    0.07       0
  5020.4    0.16       0
Bank Sta=5016.4,5020.4
Exp/Cntr=0.3,0.1

Type RM Length L Ch R = 1,2071,48,48,48
BEGIN DESCRIPTION:
elmc429
END DESCRIPTION:
XS GIS Cut Line= 3
      1515311.19      6767448.03      1515493.50      6767440.22
      1515681.15      6767389.75
#Sta/Elev= 30
  4811.0 2237.35  4834.8 2236.69  4844.8 2233.82  4864.9 2225.39  4884.9 2215.77
  4894.9 2212.44  4910.6 2208.62  4929.2 2204.53  4944.9 2199.66  4954.9 2198.14
  4965.0 2193.65  4983.0 2181.63  4983.2 2181.13  4986.7 2181.13  4987.0 2181.63
  4996.8 2182.07  5005.4 2185.28  5015.7 2187.95  5026.3 2193.38  5055.9 2202.21
  5061.1 2203.30  5077.9 2209.15  5088.2 2212.14  5108.9 2219.73  5129.7 2225.36
  5135.8 2229.57  5150.4 2235.08  5160.7 2236.84  5175.8 2241.23  5187.8 2250.61
#Mann=4,-1,0
  4811.0    0.07       0  4910.6    0.16       0  4983.0    0.07       0
  4987.0    0.16       0
Bank Sta=4983,4987
Exp/Cntr=0.3,0.1

Type RM Length L Ch R = 1,2023,63,63,63
BEGIN DESCRIPTION:
elmc427
END DESCRIPTION:
XS GIS Cut Line= 3
      1515315.13      6767479.28      1515501.32      6767487.09
      1515690.67      6767445.59
#Sta/Elev= 30
  4809.4 2232.09  4829.3 2229.36  4839.3 2226.85  4869.3 2218.03  4889.3 2210.99
  4896.2 2207.51  4901.2 2206.68  4904.0 2205.60  4949.4 2189.13  4979.4 2181.29
  4987.4 2180.19  4987.7 2179.69  4991.2 2179.69  4991.4 2180.19  4995.1 2182.15
  5000.2 2182.15  5020.0 2191.04  5030.2 2196.86  5040.5 2200.81  5058.7 2205.76
  5063.8 2200.69  5081.4 2206.77  5091.7 2211.48  5101.9 2213.08  5107.7 2215.34
  5112.8 2216.52  5132.6 2223.91  5151.5 2228.88  5163.3 2234.05  5189.6 2238.12
#Mann=4,-1,0
  4809.4    0.07       0  4904.0    0.16       0  4987.4    0.07       0
  4991.4    0.16       0
Bank Sta=4987.4,4991.4
Exp/Cntr=0.3,0.1

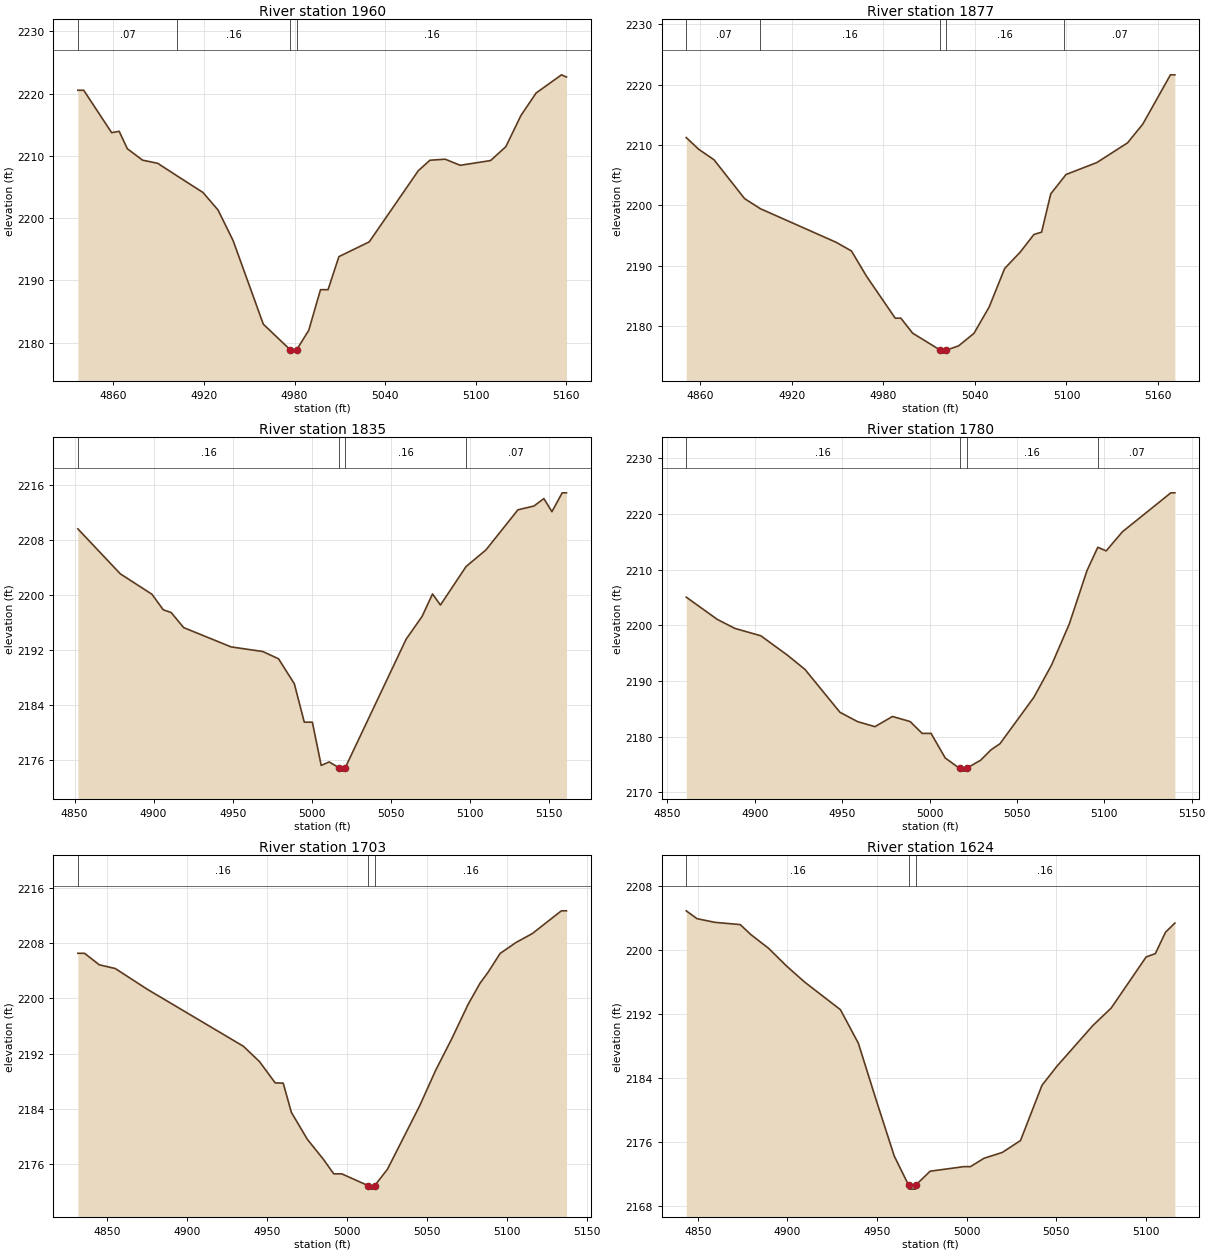
Type RM Length L Ch R = 1,1960,83,83,83
BEGIN DESCRIPTION:
elmc382
END DESCRIPTION:
XS GIS Cut Line= 3
      1515342.19      6767541.82      1515505.63      6767548.99
      1515665.02      6767532.84
#Sta/Elev= 30
  4836.4 2220.52  4840.3 2220.52  4858.8 2213.71  4863.8 2213.93  4869.2 2211.13
  4879.3 2209.29  4889.3 2208.79  4902.1 2206.78  4919.3 2204.11  4929.3 2201.29
  4939.3 2196.37  4959.3 2182.95  4977.3 2178.80  4977.6 2178.30  4981.3 2178.80
  4989.4 2181.96  4997.2 2188.49  5002.2 2188.49  5009.4 2193.80  5029.5 2196.17
  5062.0 2207.60  5069.7 2209.28  5079.8 2209.45  5089.8 2208.47  5109.9 2209.23
  5120.0 2211.45  5130.0 2216.46  5140.1 2220.09  5156.9 2223.00  5160.2 2222.65
#Mann=4,-1,0
  4836.4    0.07       0  4902.1    0.16       0  4977.3    0.07       0
  4981.3    0.16       0
Bank Sta=4977.3,4981.3
Exp/Cntr=0.3,0.1

Type RM Length L Ch R = 1,1877,42,42,42
BEGIN DESCRIPTION:
elmc426
END DESCRIPTION:
XS GIS Cut Line= 3
      1515356.80      6767631.63      1515497.41      6767632.93
      1515675.83      6767613.39
#Sta/Elev= 30
  4850.9 2211.22  4859.1 2209.27  4869.1 2207.54  4889.1 2201.11  4899.5 2199.43
  4949.1 2193.87  4959.1 2192.44  4969.1 2188.21  4987.8 2181.30  4991.5 2181.30
  4999.2 2178.82  5017.3 2176.01  5017.5 2175.51  5021.0 2175.51  5021.3 2176.01
  5029.3 2176.71  5039.4 2178.79  5049.4 2183.18  5059.5 2189.53  5069.6 2192.22
  5078.7 2195.17  5083.7 2195.55  5089.7 2201.90  5098.4 2204.68  5099.7 2205.10
  5119.9 2207.08  5140.0 2210.34  5150.0 2213.45  5168.1 2221.61  5171.0 2221.61
#Mann=5,-1,0
  4850.9    0.07       0  4899.5    0.16       0  5017.3    0.07       0
  5021.3    0.16       0  5098.4    0.07       0
Bank Sta=5017.3,5021.3
Exp/Cntr=0.3,0.1

Type RM Length L Ch R = 1,1835,55,55,55
BEGIN DESCRIPTION:
elmc425
END DESCRIPTION:
XS GIS Cut Line= 3
      1515358.11      6767671.99      1515502.62      6767674.59
      1515665.41      6767651.15
#Sta/Elev= 30
  4852.1 2209.55  4879.0 2203.00  4899.0 2200.03  4906.1 2197.78  4911.1 2197.38
  4919.0 2195.19  4949.0 2192.38  4969.0 2191.71  4979.0 2190.65  4989.0 2187.02
  4995.3 2181.43  5000.4 2181.43  5006.0 2175.14  5011.0 2175.65  5017.2 2174.81
  5017.5 2174.31  5021.0 2174.31  5021.2 2174.81  5059.7 2193.50  5069.8 2196.82
  5076.4 2200.08  5081.4 2198.47  5097.6 2204.07  5110.2 2206.49  5130.4 2212.32
  5140.5 2212.87  5146.8 2213.95  5151.9 2212.05  5158.4 2214.79  5161.1 2214.79
#Mann=4,-1,0
  4852.1    0.16       0  5017.2    0.07       0  5021.2    0.16       0
  5097.6    0.07       0
Bank Sta=5017.2,5021.2
Exp/Cntr=0.3,0.1

Type RM Length L Ch R = 1,1780,77,77,77
BEGIN DESCRIPTION:
elmc424
END DESCRIPTION:
XS GIS Cut Line= 3
      1515367.23      6767720.17      1515503.92      6767729.28
      1515644.58      6767705.84
#Sta/Elev= 30
  4860.8 2205.06  4878.6 2201.06  4888.6 2199.45  4903.5 2198.12  4918.7 2194.64
  4928.7 2192.10  4948.8 2184.38  4958.8 2182.72  4968.8 2181.81  4978.8 2183.64
  4988.9 2182.73  4995.8 2180.60  5000.9 2180.60  5009.0 2176.19  5017.2 2174.33
  5017.4 2173.83  5020.9 2173.83  5021.2 2174.33  5029.3 2175.80  5035.2 2177.66
  5040.3 2178.74  5059.7 2187.07  5069.9 2192.92  5080.0 2200.26  5090.1 2209.81
  5096.3 2214.01  5101.1 2213.36  5110.4 2216.79  5138.1 2223.78  5140.4 2223.78
#Mann=4,-1,0
  4860.8    0.16       0  5017.2    0.07       0  5021.2    0.16       0
  5096.3    0.07       0
Bank Sta=5017.2,5021.2
Exp/Cntr=0.3,0.1

Type RM Length L Ch R = 1,1703,79,79,79
BEGIN DESCRIPTION:
elmc423
END DESCRIPTION:
XS GIS Cut Line= 3
      1515351.57      6767806.11      1515513.04      6767802.20
      1515656.30      6767787.87
#Sta/Elev= 30
  4831.6 2206.56  4835.8 2206.56  4845.0 2204.89  4855.0 2204.35  4875.0 2201.34
  4935.1 2193.06  4945.1 2190.85  4955.0 2187.74  4960.0 2187.70  4965.1 2183.46
  4975.1 2179.54  4985.1 2176.65  4991.6 2174.53  4996.6 2174.53  5013.2 2172.81
  5013.4 2172.31  5016.9 2172.31  5017.2 2172.81  5025.2 2175.21  5045.3 2184.41
  5055.4 2189.61  5065.4 2194.16  5075.5 2199.10  5083.0 2202.20  5088.1 2203.81
  5095.6 2206.54  5105.6 2208.14  5115.7 2209.42  5133.9 2212.73  5137.1 2212.73
#Mann=3,-1,0
  4831.6    0.16       0  5013.2    0.07       0  5017.2    0.16       0
Bank Sta=5013.2,5017.2
Exp/Cntr=0.3,0.1

Type RM Length L Ch R = 1,1624,67,67,67
BEGIN DESCRIPTION:
elmc422
END DESCRIPTION:
XS GIS Cut Line= 3
      1515399.05      6767874.00      1515557.44      6767868.58
      1515670.13      6767851.24
#Sta/Elev= 30
  4843.6 2204.91  4849.6 2203.93  4859.6 2203.47  4873.7 2203.19  4879.6 2201.95
  4889.6 2200.21  4899.6 2198.00  4909.6 2196.01  4929.6 2192.55  4939.6 2188.35
  4949.6 2181.21  4959.6 2174.26  4967.6 2170.62  4967.9 2170.12  4971.4 2170.12
  4971.6 2170.62  4979.6 2172.36  4998.4 2172.93  5002.1 2172.93  5009.7 2173.98
  5019.9 2174.71  5030.0 2176.19  5042.0 2183.10  5050.2 2185.45  5070.4 2190.58
  5080.6 2192.76  5100.1 2199.15  5105.2 2199.56  5110.9 2202.24  5116.1 2203.38
#Mann=3,-1,0
  4843.6    0.16       0  4967.6    0.07       0  4971.6    0.16       0
Bank Sta=4967.6,4971.6
Exp/Cntr=0.3,0.1