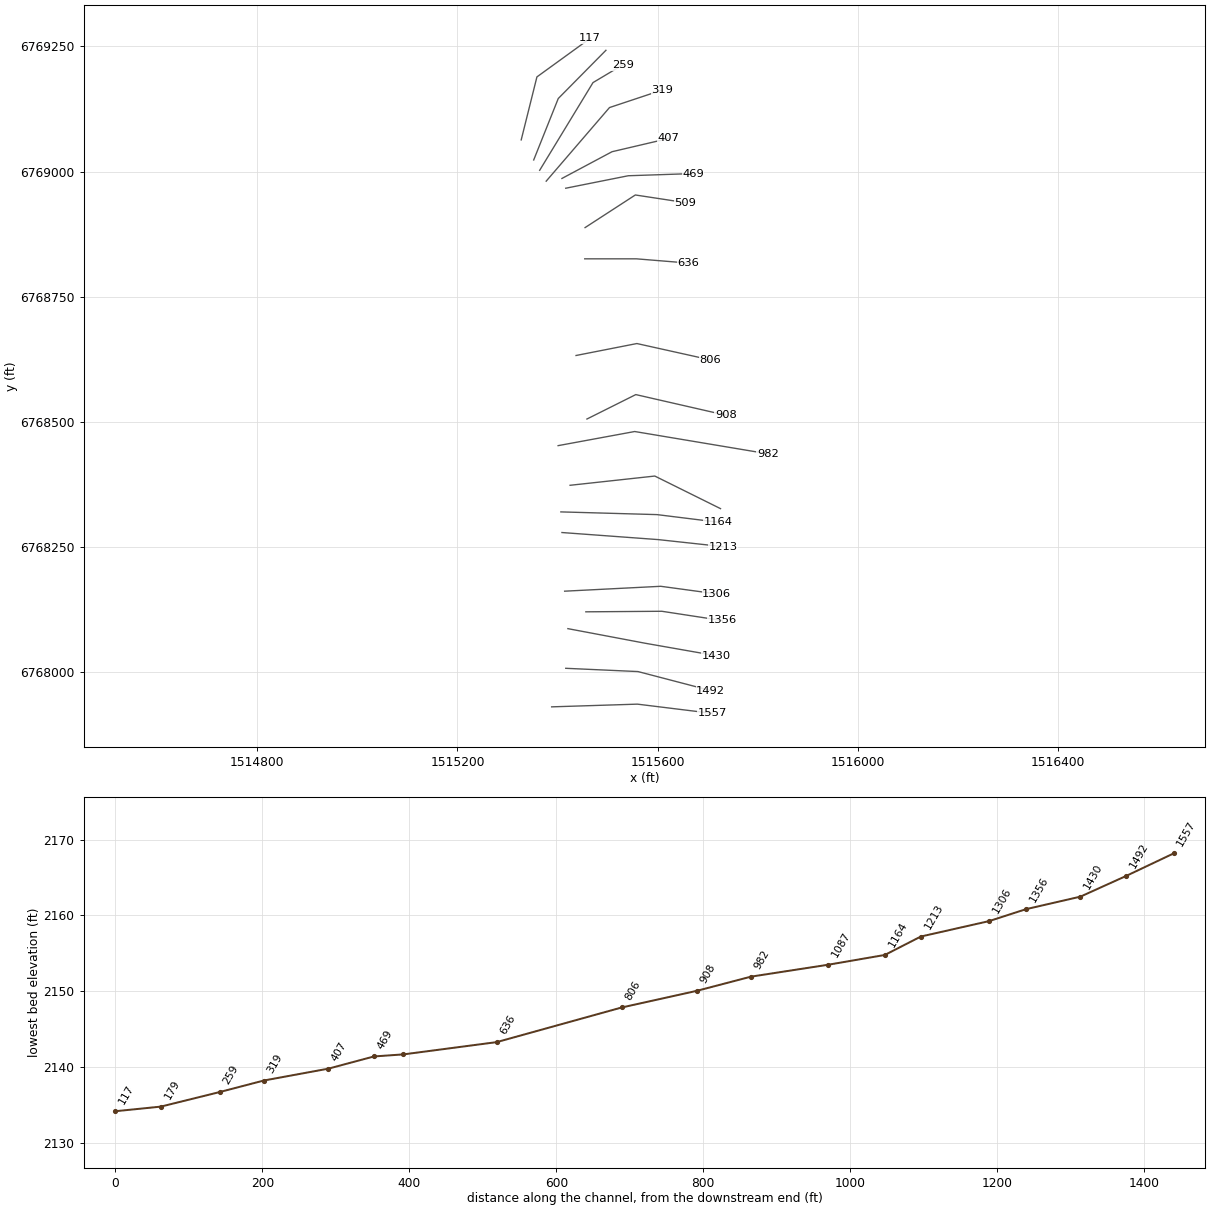
HEC-RAS study Elm 54.prj: Elm 54 Base Level Engineering

--- Elm 54.g01 (geometry) --- (continued)

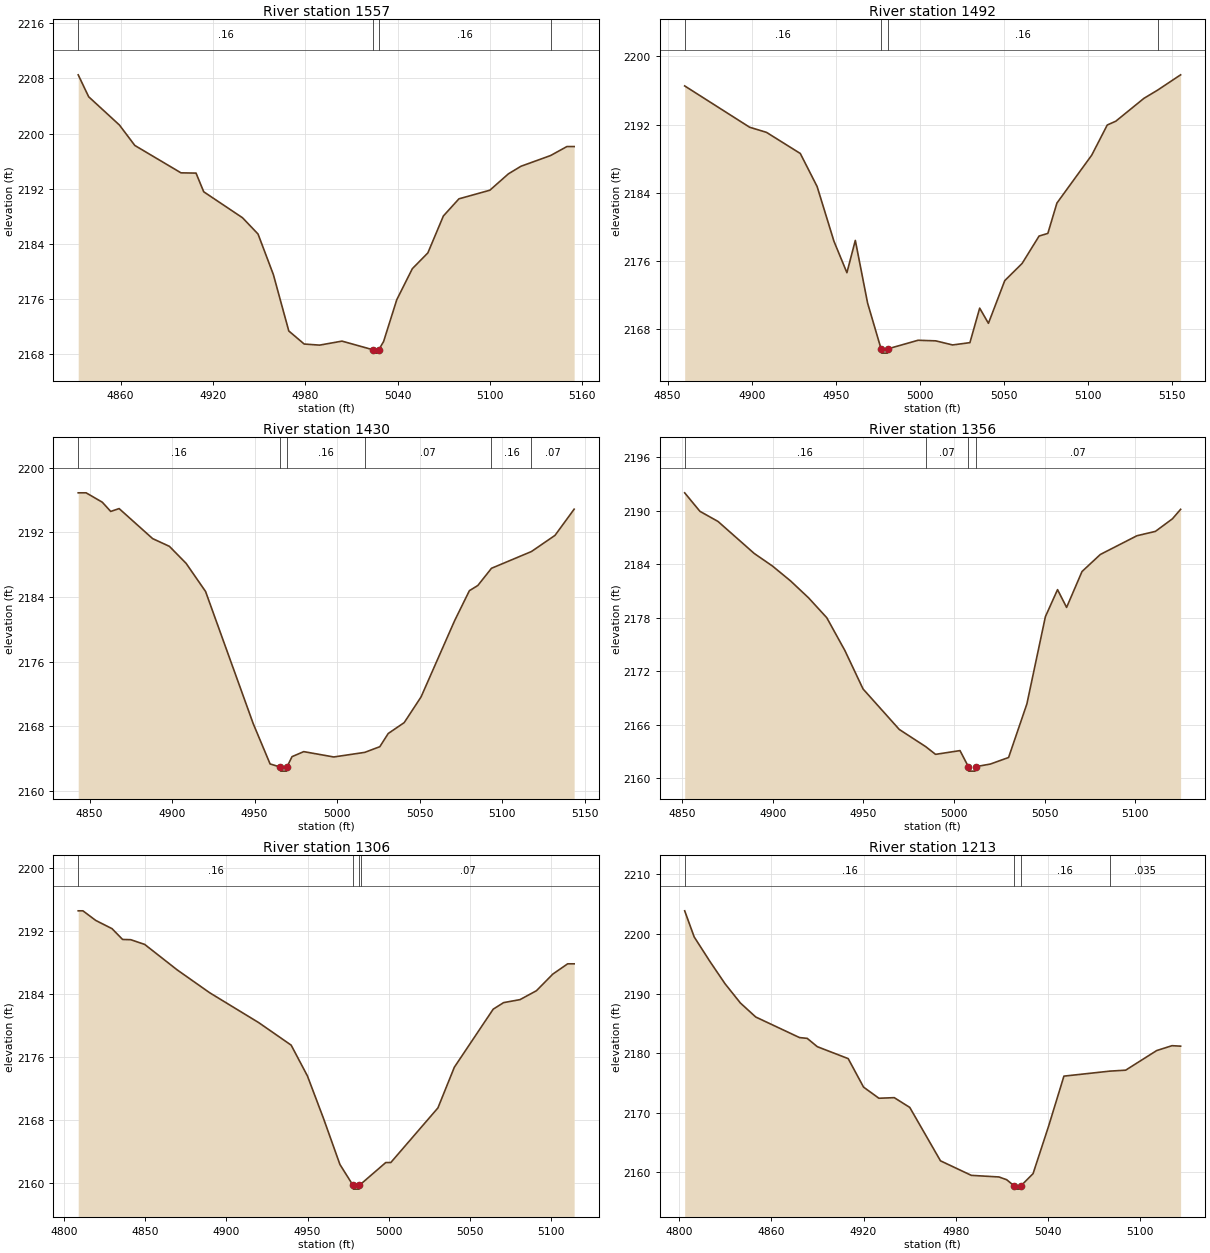
Type RM Length L Ch R = 1,1557,65,65,65
BEGIN DESCRIPTION:
elmc421
END DESCRIPTION:
XS GIS Cut Line= 3
      1515388.21      6767930.43      1515559.61      6767935.85
      1515709.39      6767917.40
#Sta/Elev= 30
  4832.4 2208.52  4839.2 2205.34  4859.2 2201.24  4869.2 2198.28  4899.2 2194.31
  4909.0 2194.27  4914.0 2191.56  4939.2 2187.80  4949.3 2185.44  4959.3 2179.54
  4969.3 2171.38  4979.3 2169.49  4989.3 2169.33  5003.9 2169.91  5023.8 2168.67
  5024.1 2168.17  5027.6 2168.17  5027.8 2168.67  5030.9 2169.84  5039.5 2175.92
  5049.6 2180.41  5059.7 2182.70  5069.8 2188.06  5079.9 2190.54  5100.0 2191.79
  5112.1 2194.17  5120.2 2195.26  5139.5 2196.82  5150.1 2198.12  5154.8 2198.12
#Mann=4,-1,0
  4832.4    0.16       0  5023.8    0.07       0  5027.8    0.16       0
  5139.5    0.07       0
Bank Sta=5023.8,5027.8
Exp/Cntr=0.3,0.1

Type RM Length L Ch R = 1,1492,62,62,62
BEGIN DESCRIPTION:
elmc420
END DESCRIPTION:
XS GIS Cut Line= 3
      1515416.42      6768007.46      1515560.70      6768000.95
      1515706.09      6767962.98
#Sta/Elev= 30
  4860.2 2196.54  4898.8 2191.69  4908.8 2191.09  4928.9 2188.61  4938.9 2184.73
  4948.9 2178.31  4956.6 2174.62  4961.6 2178.41  4968.9 2171.05  4976.9 2165.68
  4977.2 2165.18  4980.7 2165.18  4980.9 2165.68  4998.9 2166.69  5009.4 2166.62
  5019.4 2166.14  5029.7 2166.41  5035.5 2170.46  5040.7 2168.68  5050.4 2173.69
  5060.7 2175.70  5070.8 2178.92  5076.0 2179.23  5081.4 2182.79  5102.1 2188.42
  5111.3 2191.95  5116.4 2192.40  5133.1 2195.08  5141.2 2196.04  5154.9 2197.84
#Mann=4,-1,0
  4860.2    0.16       0  4976.9    0.07       0  4980.9    0.16       0
  5141.2    0.07       0
Bank Sta=4976.9,4980.9
Exp/Cntr=0.3,0.1

Type RM Length L Ch R = 1,1430,74,74,74
BEGIN DESCRIPTION:
elmc419
END DESCRIPTION:
XS GIS Cut Line= 3
      1515420.70      6768086.68      1515575.89      6768057.38
      1515716.40      6768032.71
#Sta/Elev= 30
  4843.1 2196.87  4847.9 2196.87  4857.7 2195.71  4862.8 2194.57  4867.9 2194.92
  4888.2 2191.21  4898.4 2190.25  4908.5 2188.15  4920.3 2184.67  4949.2 2168.32
  4959.4 2163.35  4965.6 2162.96  4965.9 2162.46  4969.4 2162.46  4969.6 2162.96
  4972.7 2164.25  4979.8 2164.87  4998.0 2164.21  5016.8 2164.78  5025.9 2165.48
  5031.0 2167.11  5040.7 2168.46  5050.9 2171.63  5071.2 2181.04  5080.2 2184.77
  5085.3 2185.41  5093.6 2187.54  5117.8 2189.61  5132.1 2191.61  5143.7 2194.85
#Mann=6,-1,0
  4843.1    0.16       0  4965.6    0.07       0  4969.6    0.16       0
  5016.8    0.07       0  5093.6    0.16       0  5117.8    0.07       0
Bank Sta=4965.6,4969.6
Exp/Cntr=0.3,0.1

Type RM Length L Ch R = 1,1356,50,50,50
BEGIN DESCRIPTION:
elmc418
END DESCRIPTION:
XS GIS Cut Line= 3
      1515456.58      6768120.31      1515608.44      6768121.40
      1515728.77      6768102.97
#Sta/Elev= 30
  4851.4 2192.00  4859.8 2189.93  4869.8 2188.79  4889.8 2185.20  4899.8 2183.80
  4909.8 2182.13  4919.8 2180.22  4929.8 2178.00  4939.8 2174.32  4949.8 2170.02
  4969.8 2165.48  4984.4 2163.55  4989.8 2162.69  5003.3 2163.11  5007.9 2161.31
  5008.1 2160.81  5011.6 2160.81  5011.9 2161.31  5020.0 2161.60  5030.1 2162.34
  5040.2 2168.35  5050.4 2178.12  5057.1 2181.15  5062.1 2179.16  5070.6 2183.18
  5080.7 2185.09  5100.9 2187.19  5111.1 2187.68  5120.5 2189.09  5125.0 2190.15
#Mann=4,-1,0
  4851.4    0.16       0  4984.4    0.07       0  5007.9    0.07       0
  5011.9    0.07       0
Bank Sta=5007.9,5011.9
Exp/Cntr=0.3,0.1

Type RM Length L Ch R = 1,1306,93,93,93
BEGIN DESCRIPTION:
elmc417
END DESCRIPTION:
XS GIS Cut Line= 3
      1515414.19      6768161.54      1515606.27      6768171.31
      1515718.01      6768156.12
#Sta/Elev= 30
  4808.9 2194.53  4811.8 2194.53  4819.7 2193.31  4829.7 2192.27  4836.2 2190.90
  4841.2 2190.87  4849.8 2190.27  4869.8 2187.04  4889.8 2184.14  4919.9 2180.36
  4939.9 2177.50  4949.9 2173.60  4959.9 2168.15  4969.9 2162.37  4977.9 2159.74
  4978.2 2159.24  4981.7 2159.24  4981.9 2159.74  4983.1 2159.94  4998.1 2162.61
  5001.2 2162.61  5030.2 2169.54  5040.3 2174.70  5064.2 2182.06  5070.6 2182.89
  5080.7 2183.27  5090.8 2184.40  5100.9 2186.51  5110.0 2187.81  5114.0 2187.81
#Mann=4,-1,0
  4808.9    0.16       0  4977.9    0.07       0  4981.9    0.16       0
  4983.1    0.07       0
Bank Sta=4977.9,4981.9
Exp/Cntr=0.3,0.1

Type RM Length L Ch R = 1,1213,49,49,49
BEGIN DESCRIPTION:
elmc416
END DESCRIPTION:
XS GIS Cut Line= 3
      1515408.82      6768278.73      1515600.85      6768264.63
      1515730.54      6768250.58
#Sta/Elev= 30
  4803.5 2203.90  4809.7 2199.52  4819.7 2195.50  4829.8 2191.66  4839.8 2188.43
  4849.8 2186.08  4878.3 2182.63  4883.3 2182.50  4889.9 2181.10  4910.0 2179.10
  4920.0 2174.32  4930.0 2172.45  4940.0 2172.55  4950.1 2170.91  4970.1 2161.95
  4990.2 2159.51  5008.2 2159.24  5013.2 2158.78  5018.3 2157.70  5018.6 2157.20
  5022.1 2157.20  5022.3 2157.70  5030.4 2159.80  5040.5 2167.75  5050.5 2176.16
  5080.4 2177.00  5090.7 2177.16  5110.9 2180.45  5120.9 2181.27  5126.5 2181.19
#Mann=4,-1,0
  4803.5    0.16       0  5018.3    0.07       0  5022.3    0.16       0
  5080.4   0.035       0
Bank Sta=5018.3,5022.3
Exp/Cntr=0.3,0.1

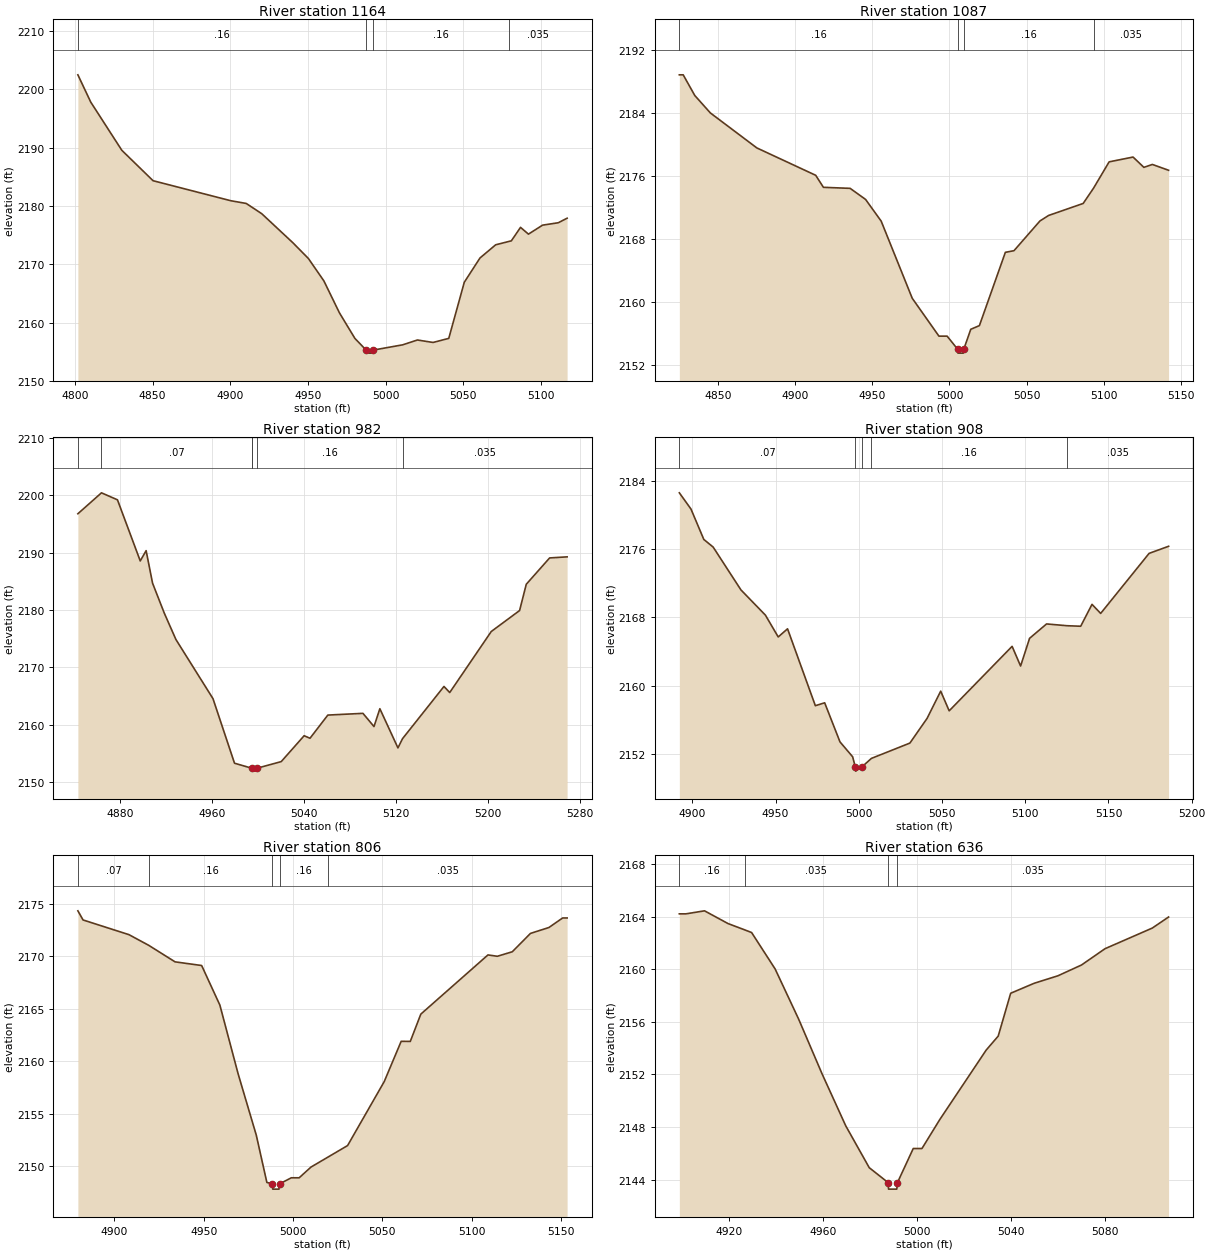
Type RM Length L Ch R = 1,1164,77,77,77
BEGIN DESCRIPTION:
elmc415
END DESCRIPTION:
XS GIS Cut Line= 3
      1515406.66      6768319.96      1515598.68      6768314.54
      1515720.66      6768299.43
#Sta/Elev= 30
  4801.9 2202.48  4810.2 2197.80  4830.2 2189.54  4850.3 2184.33  4900.3 2180.90
  4910.3 2180.43  4920.3 2178.67  4940.3 2173.70  4950.3 2171.00  4960.3 2167.15
  4970.3 2161.68  4980.3 2157.28  4987.6 2155.27  4987.9 2154.77  4991.4 2154.77
  4991.6 2155.27  5011.0 2156.19  5020.5 2157.02  5030.6 2156.60  5040.7 2157.30
  5050.7 2166.92  5060.8 2171.08  5070.9 2173.34  5079.3 2173.91  5081.0 2174.02
  5086.9 2176.33  5092.0 2175.17  5101.1 2176.71  5111.2 2177.12  5116.9 2177.90
#Mann=4,-1,0
  4801.9    0.16       0  4987.6    0.07       0  4991.6    0.16       0
  5079.3   0.035       0
Bank Sta=4987.6,4991.6
Exp/Cntr=0.3,0.1

Type RM Length L Ch R = 1,1087,105,105,105
BEGIN DESCRIPTION:
elmc413
END DESCRIPTION:
XS GIS Cut Line= 3
      1515425.06      6768373.13      1515594.34      6768391.58
      1515725.61      6768326.49
#Sta/Elev= 30
  4825.1 2188.88  4827.6 2188.88  4835.1 2186.25  4845.2 2184.03  4875.3 2179.58
  4913.4 2176.10  4918.4 2174.57  4935.7 2174.44  4945.7 2173.03  4955.8 2170.27
  4975.9 2160.46  4993.2 2155.64  4998.5 2155.64  5005.3 2153.98  5005.5 2153.48
  5009.0 2153.48  5009.3 2153.98  5013.8 2156.51  5019.4 2156.98  5036.2 2166.30
  5041.8 2166.51  5058.6 2170.29  5064.2 2170.99  5086.6 2172.52  5093.3 2174.46
  5103.4 2177.81  5118.9 2178.42  5125.9 2177.11  5131.4 2177.48  5141.9 2176.74
#Mann=4,-1,0
  4825.1    0.16       0  5005.3    0.07       0  5009.3    0.16       0
  5093.3   0.035       0
Bank Sta=5005.3,5009.3
Exp/Cntr=0.3,0.1

Type RM Length L Ch R = 1,982,74,74,74
BEGIN DESCRIPTION:
elmc414
END DESCRIPTION:
XS GIS Cut Line= 3
      1515401.18      6768452.34      1515554.19      6768480.56
      1515820.01      6768436.07
#Sta/Elev= 30
  4843.5 2196.77  4864.0 2200.42  4877.9 2199.20  4897.7 2188.55  4902.8 2190.34
  4908.4 2184.67  4918.6 2179.44  4928.7 2174.85  4960.9 2164.54  4979.6 2153.29
  4994.4 2152.43  4995.0 2152.41  4995.2 2151.91  4999.0 2152.41  5020.2 2153.57
  5040.1 2158.08  5045.2 2157.64  5060.7 2161.68  5091.2 2161.98  5100.8 2159.68
  5105.9 2162.79  5121.6 2155.96  5125.6 2157.57  5161.6 2166.67  5166.6 2165.61
  5202.7 2176.25  5227.3 2179.90  5233.1 2184.48  5253.4 2189.07  5268.6 2189.26
#Mann=6,-1,0
  4843.5    0.16       0  4864.0    0.07       0  4994.4    0.16       0
  4995.0    0.07       0  4999.0    0.16       0  5125.6   0.035       0
Bank Sta=4995,4999
Exp/Cntr=0.3,0.1

Type RM Length L Ch R = 1,908,102,102,102
BEGIN DESCRIPTION:
elmc411
END DESCRIPTION:
XS GIS Cut Line= 3
      1515458.72      6768505.52      1515556.36      6768554.34
      1515736.44      6768513.12
#Sta/Elev= 30
  4892.2 2182.57  4899.2 2180.67  4906.9 2177.12  4912.5 2176.23  4929.2 2171.22
  4943.9 2168.27  4951.6 2165.72  4957.2 2166.67  4973.9 2157.68  4979.5 2158.02
  4988.7 2153.45  4996.3 2151.71  4997.9 2150.53  4998.1 2150.03  5001.9 2150.53
  5007.6 2151.52  5030.7 2153.31  5041.0 2156.19  5049.2 2159.38  5054.3 2157.08
  5092.1 2164.62  5097.2 2162.32  5102.6 2165.56  5112.8 2167.24  5125.2 2167.03
  5133.3 2166.97  5140.1 2169.53  5145.3 2168.47  5174.4 2175.49  5186.1 2176.32
#Mann=5,-1,0
  4892.2    0.07       0  4997.9    0.07       0  5001.9    0.07       0
  5007.6    0.16       0  5125.2   0.035       0
Bank Sta=4997.9,5001.9
Exp/Cntr=0.3,0.1

Type RM Length L Ch R = 1,806,170,170,170
BEGIN DESCRIPTION:
elmc412
END DESCRIPTION:
XS GIS Cut Line= 3
      1515436.98      6768632.46      1515558.53      6768656.34
      1515704.98      6768623.79
#Sta/Elev= 30
  4879.5 2174.35  4882.4 2173.48  4908.1 2172.08  4919.2 2171.06  4933.9 2169.49
  4948.8 2169.14  4959.0 2165.37  4969.2 2158.83  4979.4 2152.97  4985.3 2148.48
  4988.4 2148.34  4988.6 2147.84  4992.1 2147.84  4992.4 2148.34  4999.0 2148.92
  5003.4 2148.92  5010.0 2149.94  5019.8 2150.92  5030.5 2151.99  5051.0 2158.08
  5060.5 2161.92  5065.6 2161.91  5071.5 2164.51  5109.1 2170.15  5114.3 2170.02
  5122.7 2170.45  5132.9 2172.20  5143.2 2172.76  5150.9 2173.67  5153.4 2173.67
#Mann=5,-1,0
  4879.5    0.07       0  4919.2    0.16       0  4988.4    0.07       0
  4992.4    0.16       0  5019.8   0.035       0
Bank Sta=4988.4,4992.4
Exp/Cntr=0.3,0.1

Type RM Length L Ch R = 1,636,127,127,127
BEGIN DESCRIPTION:
elmc410
END DESCRIPTION:
XS GIS Cut Line= 3
      1515454.34      6768825.61      1515557.44      6768825.61
      1515661.89      6768817.08
#Sta/Elev= 27
  4899.0 2164.21  4901.8 2164.21  4909.7 2164.44  4919.7 2163.47  4926.8 2162.99
  4929.7 2162.79  4939.7 2160.02  4949.7 2156.20  4959.7 2152.02  4969.7 2148.09
  4979.7 2144.90  4987.7 2143.77  4987.9 2143.27  4991.4 2143.27  4991.7 2143.77
  4998.4 2146.36  5002.1 2146.36  5009.7 2148.57  5029.4 2153.85  5034.5 2154.91
  5039.8 2158.17  5049.8 2158.93  5059.9 2159.50  5069.9 2160.32  5079.9 2161.56
  5100.0 2163.13  5106.9 2163.97
#Mann=4,-1,0
  4899.0    0.16       0  4926.8   0.035       0  4987.7   0.035       0
  4991.7   0.035       0
Bank Sta=4987.7,4991.7
Exp/Cntr=0.3,0.1

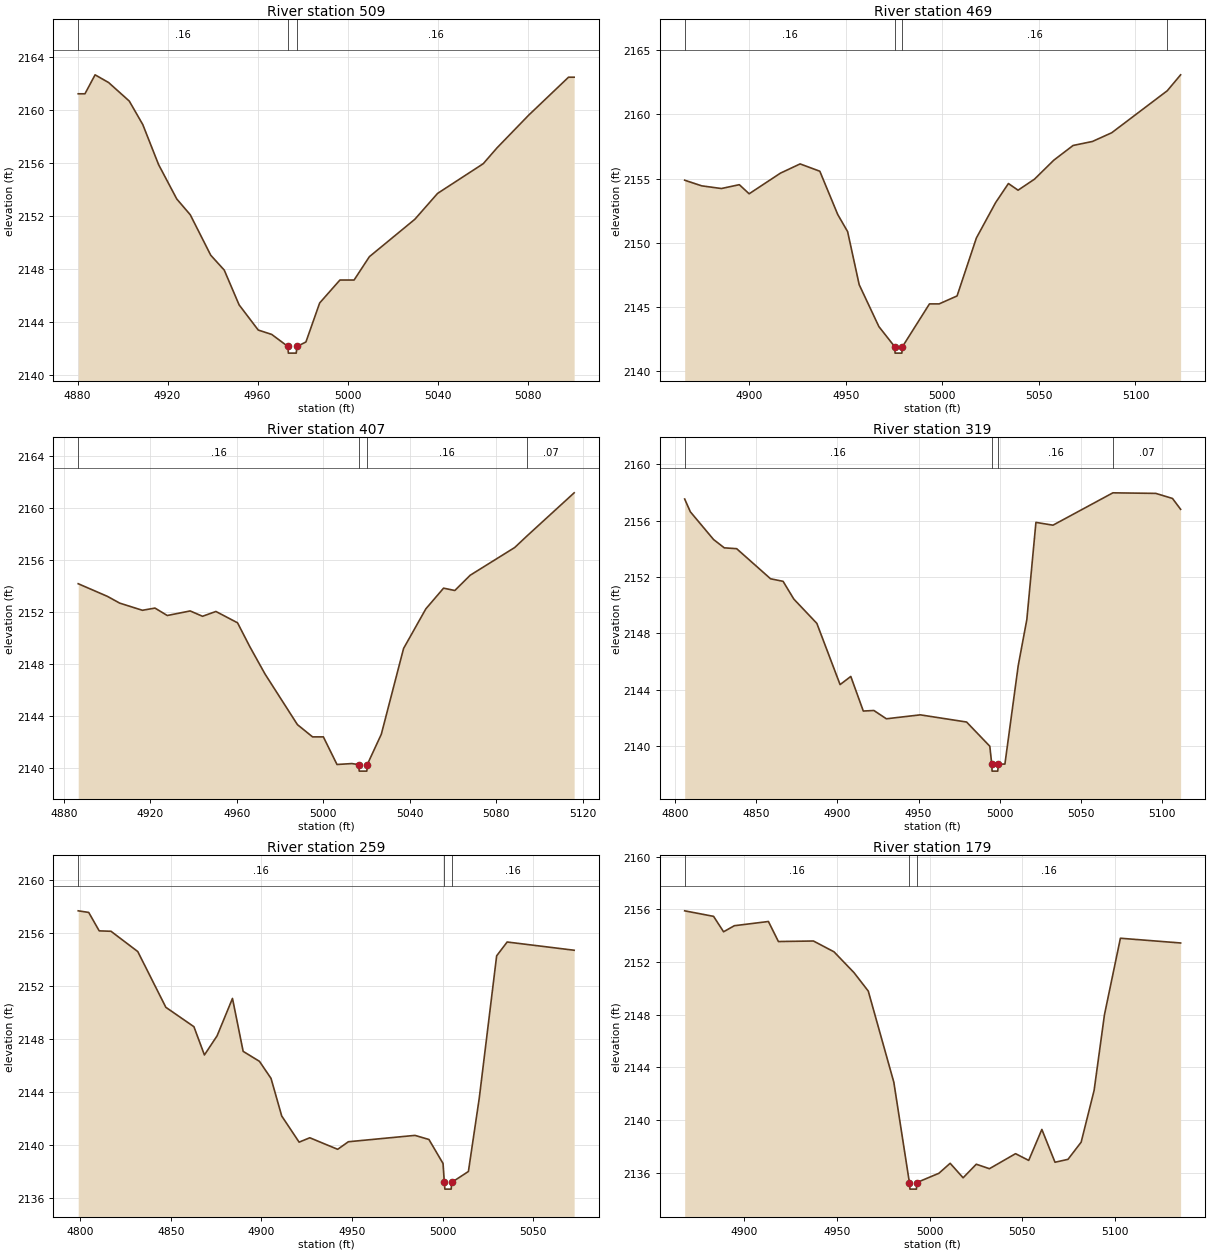
Type RM Length L Ch R = 1,509,40,40,40
BEGIN DESCRIPTION:
elmc381
END DESCRIPTION:
XS GIS Cut Line= 3
      1515455.02      6768888.01      1515555.43      6768953.18
      1515654.98      6768938.00
#Sta/Elev= 30
  4880.3 2161.20  4883.3 2161.20  4887.8 2162.63  4893.8 2162.05  4903.0 2160.65
  4909.0 2158.88  4916.0 2155.87  4924.1 2153.27  4930.1 2152.08  4939.2 2149.03
  4945.2 2147.91  4951.8 2145.29  4960.3 2143.39  4966.3 2143.06  4973.5 2142.15
  4973.7 2141.65  4977.2 2141.65  4977.5 2142.15  4981.5 2142.49  4987.6 2145.43
  4996.6 2147.16  5002.9 2147.16  5009.7 2148.92  5029.9 2151.74  5040.0 2153.69
  5060.3 2155.93  5066.4 2157.12  5080.5 2159.59  5098.2 2162.45  5100.7 2162.45
#Mann=3,-1,0
  4880.3    0.16       0  4973.5    0.07       0  4977.5    0.16       0
Bank Sta=4973.5,4977.5
Exp/Cntr=0.3,0.1

Type RM Length L Ch R = 1,469,62,62,62
BEGIN DESCRIPTION:
elmc409
END DESCRIPTION:
XS GIS Cut Line= 3
      1515416.34      6768966.66      1515541.34      6768991.60
      1515670.71      6768995.94
#Sta/Elev= 30
  4866.5 2154.87  4875.3 2154.43  4885.5 2154.22  4894.8 2154.52  4899.9 2153.81
  4916.1 2155.42  4926.3 2156.14  4936.5 2155.57  4945.8 2152.19  4950.9 2150.86
  4956.9 2146.72  4967.1 2143.45  4975.3 2141.88  4975.5 2141.38  4979.0 2141.38
  4979.3 2141.88  4993.3 2145.22  4998.3 2145.22  5007.6 2145.84  5017.6 2150.36
  5027.6 2153.13  5034.2 2154.61  5039.2 2154.09  5047.7 2154.95  5057.7 2156.43
  5067.7 2157.58  5077.7 2157.89  5087.7 2158.57  5116.5 2161.85  5123.4 2163.09
#Mann=4,-1,0
  4866.5    0.16       0  4975.3    0.07       0  4979.3    0.16       0
  5116.5   0.035       0
Bank Sta=4975.3,4979.3
Exp/Cntr=0.3,0.1

Type RM Length L Ch R = 1,407,88,88,88
BEGIN DESCRIPTION:
elmc408
END DESCRIPTION:
XS GIS Cut Line= 3
      1515408.82      6768986.21      1515508.86      6769039.60
      1515621.80      6769066.06
#Sta/Elev= 30
  4886.6 2154.16  4900.1 2153.19  4905.8 2152.67  4916.3 2152.12  4922.1 2152.29
  4927.8 2151.72  4938.4 2152.07  4944.1 2151.66  4950.3 2152.03  4960.3 2151.16
  4966.0 2149.32  4973.0 2147.23  4988.0 2143.34  4995.0 2142.40  5000.0 2142.40
  5006.3 2140.28  5013.2 2140.35  5016.3 2140.27  5016.6 2139.77  5020.1 2139.77
  5020.3 2140.27  5026.8 2142.60  5037.1 2149.19  5047.4 2152.23  5055.6 2153.82
  5060.8 2153.64  5067.9 2154.81  5088.5 2156.94  5094.2 2157.83  5116.0 2161.14
#Mann=4,-1,0
  4886.6    0.16       0  5016.3    0.07       0  5020.3    0.16       0
  5094.2    0.07       0
Bank Sta=5016.3,5020.3
Exp/Cntr=0.3,0.1

Type RM Length L Ch R = 1,319,60,60,60
BEGIN DESCRIPTION:
elmc407
END DESCRIPTION:
XS GIS Cut Line= 3
      1515377.32      6768980.77      1515503.84      6769127.85
      1515609.54      6769163.01
#Sta/Elev= 30
  4806.0 2157.54  4809.5 2156.63  4823.8 2154.66  4830.4 2154.07  4838.0 2154.01
  4858.9 2151.87  4866.6 2151.69  4873.2 2150.43  4887.4 2148.70  4901.7 2144.35
  4908.3 2144.93  4916.0 2142.47  4922.5 2142.51  4930.2 2141.92  4951.1 2142.20
  4979.6 2141.69  4993.9 2139.97  4995.1 2138.70  4995.3 2138.20  4998.8 2138.20
  4999.1 2138.70  5003.2 2138.70  5011.4 2145.70  5016.7 2148.97  5022.3 2155.88
  5032.8 2155.68  5069.7 2157.98  5096.1 2157.94  5106.4 2157.58  5111.4 2156.81
#Mann=4,-1,0
  4806.0    0.16       0  4995.1    0.07       0  4999.1    0.16       0
  5069.7    0.07       0
Bank Sta=4995.1,4999.1
Exp/Cntr=0.3,0.1

Type RM Length L Ch R = 1,259,80,80,80
BEGIN DESCRIPTION:
elmc406
END DESCRIPTION:
XS GIS Cut Line= 3
      1515364.32      6769002.50      1515470.89      6769177.74
      1515529.97      6769212.98
#Sta/Elev= 30
  4798.8 2157.65  4804.6 2157.53  4810.4 2156.14  4816.9 2156.11  4831.7 2154.58
  4847.2 2150.38  4862.7 2148.92  4868.5 2146.79  4875.5 2148.23  4884.0 2151.05
  4889.9 2147.06  4898.9 2146.31  4905.3 2145.02  4911.2 2142.19  4920.8 2140.22
  4926.7 2140.55  4942.1 2139.68  4948.0 2140.25  4984.8 2140.73  4992.5 2140.42
  5000.3 2138.61  5001.0 2137.18  5001.3 2136.68  5004.8 2136.68  5005.0 2137.18
  5014.3 2138.01  5020.3 2143.54  5029.9 2154.26  5035.7 2155.30  5072.7 2154.68
#Mann=3,-1,0
  4798.8    0.16       0  5001.0    0.07       0  5005.0    0.16       0
Bank Sta=5001,5005
Exp/Cntr=0.3,0.1

Type RM Length L Ch R = 1,179,62,62,62
BEGIN DESCRIPTION:
elmc405
END DESCRIPTION:
XS GIS Cut Line= 3
      1515352.38      6769023.12      1515401.43      6769145.88
      1515496.67      6769242.27
#Sta/Elev= 30
  4867.8 2155.88  4883.4 2155.46  4888.8 2154.29  4894.6 2154.75  4913.0 2155.07
  4918.4 2153.55  4937.3 2153.59  4948.4 2152.77  4959.2 2151.19  4966.9 2149.79
  4980.7 2142.87  4989.1 2135.26  4989.4 2134.76  4992.9 2134.76  4993.1 2135.26
  5005.0 2135.96  5011.1 2136.72  5018.1 2135.62  5025.2 2136.65  5032.3 2136.31
  5046.4 2137.45  5053.5 2136.94  5060.6 2139.29  5067.7 2136.80  5074.7 2137.02
  5081.8 2138.32  5088.8 2142.25  5094.4 2148.00  5103.0 2153.80  5135.5 2153.44
#Mann=3,-1,0
  4867.8    0.16       0  4989.1    0.07       0  4993.1    0.16       0
Bank Sta=4989.1,4993.1
Exp/Cntr=0.3,0.1

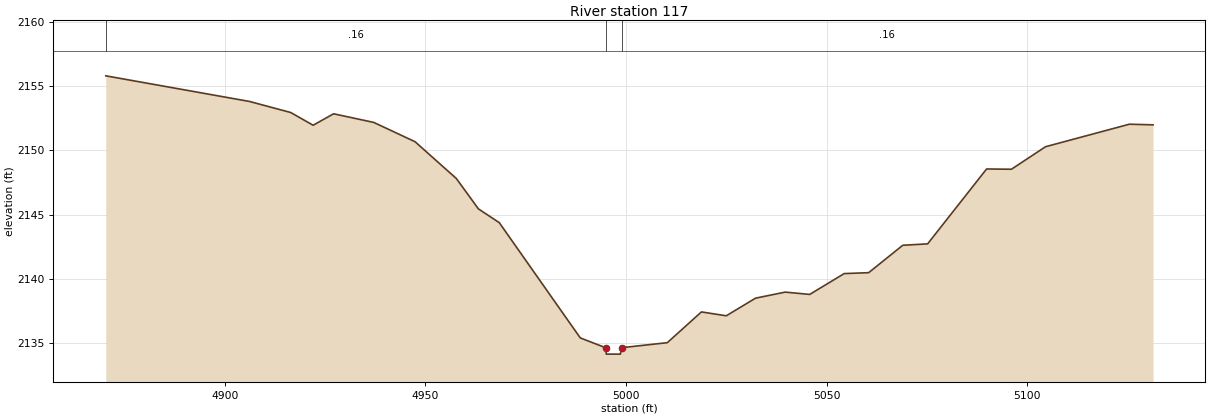
Type RM Length L Ch R = 1,117,0,0,0
BEGIN DESCRIPTION:
elmc404
END DESCRIPTION:
XS GIS Cut Line= 3
      1515327.41      6769063.23      1515358.81      6769189.07
      1515465.22      6769266.15
#Sta/Elev= 30
  4870.3 2155.78  4906.1 2153.79  4916.4 2152.93  4922.0 2151.94  4927.1 2152.83
  4937.1 2152.16  4947.4 2150.66  4957.7 2147.80  4963.2 2145.44  4968.4 2144.37
  4988.6 2135.41  4994.9 2134.65  4995.1 2134.15  4998.6 2134.15  4998.9 2134.65
  5010.3 2135.04  5018.8 2137.43  5025.0 2137.13  5032.3 2138.50  5039.7 2138.97
  5045.8 2138.79  5054.4 2140.41  5060.5 2140.48  5069.0 2142.61  5075.2 2142.72
  5089.9 2148.54  5096.1 2148.52  5104.6 2150.27  5125.5 2152.02  5131.4 2151.97
#Mann=3,-1,0
  4870.3    0.16       0  4994.9    0.07       0  4998.9    0.16       0
Bank Sta=4994.9,4998.9
Exp/Cntr=0.3,0.1

Chan Stop Cuts=-1