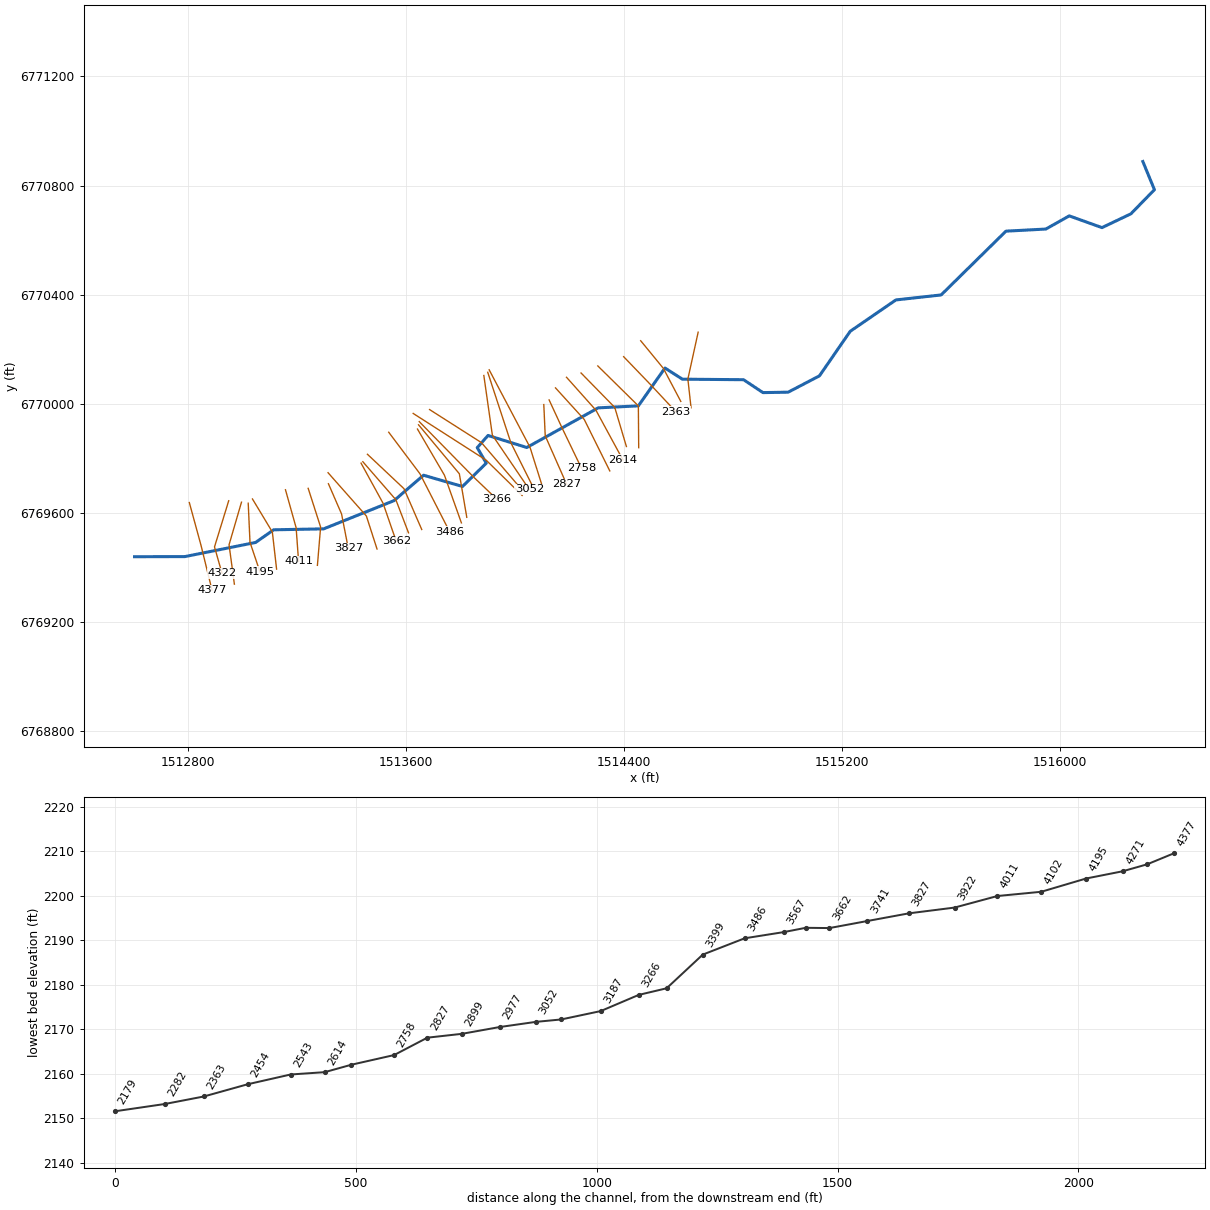
--- Elm 55.prj (project) ---

Proj Title=Elm 55 Base Level Engineering
Current Plan=p01
Default Exp/Contr=0.3,0.1
English Units
Geom File=g01
Flow File=f01
Plan File=p01
BEGIN DESCRIPTION:
Elm 55
END DESCRIPTION:

--- Elm 55.p01 (plan) ---

Plan Title=Multiple Run
Short Identifier=Multiple
Geom File=g01
Flow File=f01
Subcritical Flow
K Sum by GR= 0
Std Step Tol= 0.01
Critical Tol= 0.01
Num of Std Step Trials= 20
Max Error Tol= 0.3
Flow Tol Ratio= 0.001
Split Flow NTrial= 30
Split Flow Tol= 0.02
Split Flow Ratio= 0.02
Log Output Level= 0
Friction Slope Method= 1
Unsteady Friction Slope Method= 2
Unsteady Bridges Friction Slope Method= 1
Parabolic Critical Depth
Global Vel Dist=  1 , 1 , 1
Global Log Level= 0
CheckData=True
Encroach Param= -1, 0, 0, 0
BEGIN DESCRIPTION:
Multiple Run
END DESCRIPTION:

--- Elm 55.f01 (steady flow) ---

Flow Title=Multiple
Number of Profiles=7
Profile Names=10-year,25-year,50-year,1pct_min,100-year,1pct_plu,500-year
River Rch & RM= Elm 55,Reach-1,4377
     200     278     344     265     425     585     655
Boundary for River Rch & Prof#=Elm 55,Reach-1,1
Up Type=0
Dn Type=3
Dn Slope=0.005
Boundary for River Rch & Prof#=Elm 55,Reach-1,2
Up Type=0
Dn Type=3
Dn Slope=0.005
Boundary for River Rch & Prof#=Elm 55,Reach-1,3
Up Type=0
Dn Type=3
Dn Slope=0.005
Boundary for River Rch & Prof#=Elm 55,Reach-1,4
Up Type=0
Dn Type=3
Dn Slope=0.005
Boundary for River Rch & Prof#=Elm 55,Reach-1,5
Up Type=0
Dn Type=3
Dn Slope=0.005
Boundary for River Rch & Prof#=Elm 55,Reach-1,6
Up Type=0
Dn Type=3
Dn Slope=0.005
Boundary for River Rch & Prof#=Elm 55,Reach-1,7
Up Type=0
Dn Type=3
Dn Slope=0.005

--- Elm 55.g01 (geometry) ---

Geom Title=Existing Conditions

River Reach=Elm 55,Reach-1
Reach XY= 30
      1512605.00      6769438.00      1512789.79      6769438.51
      1513049.06      6769490.26      1513115.51      6769536.78
      1513299.06      6769540.26      1513557.29      6769643.85
      1513665.49      6769737.05      1513808.45      6769695.80
      1513895.69      6769781.30      1513862.47      6769838.28
      1513902.16      6769882.91      1514044.31      6769838.75
      1514306.56      6769984.24      1514453.75      6769991.46
      1514551.33      6770130.31      1514615.43      6770089.39
      1514839.78      6770087.48      1514910.98      6770040.17
      1515003.42      6770041.67      1515118.24      6770101.61
      1515231.16      6770265.14      1515398.82      6770380.17
      1515564.80      6770398.48      1515802.55      6770632.53
      1515949.06      6770640.27      1516034.96      6770688.58
      1516155.01      6770645.53      1516261.09      6770696.12
      1516347.42      6770784.59      1516305.00      6770888.00

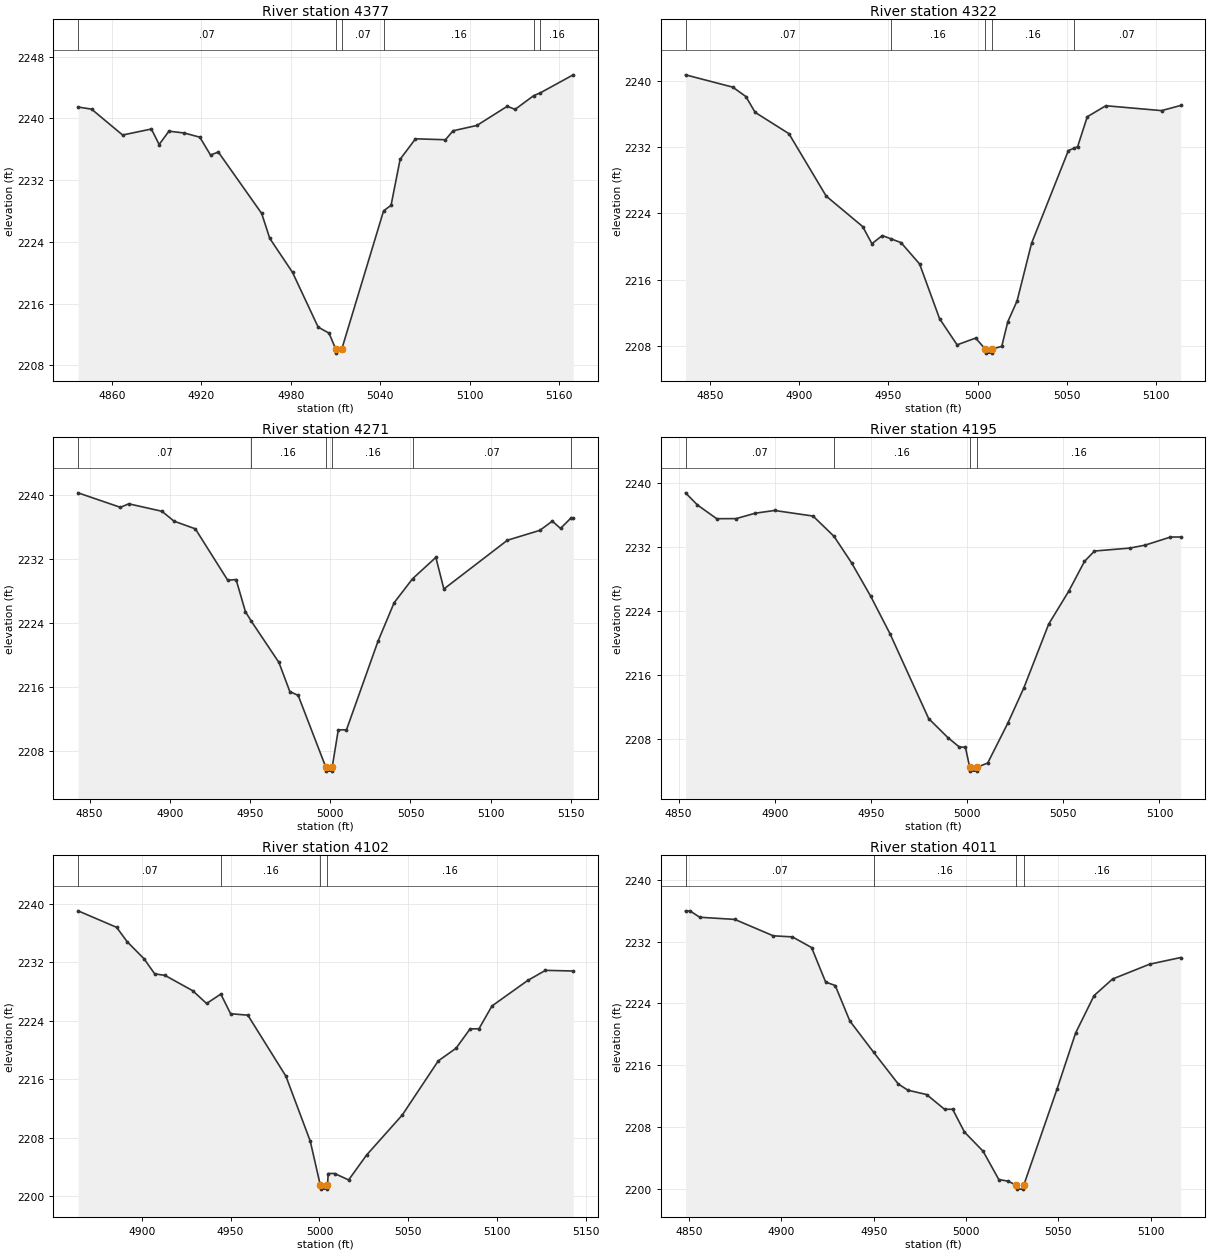
Type RM Length L Ch R = 1,4377,55,55,55
BEGIN DESCRIPTION:
elmc393
END DESCRIPTION:
XS GIS Cut Line= 3
      1512806.02      6769636.79      1512848.94      6769479.86
      1512889.33      6769315.24
#Sta/Elev= 30
  4837.3 2241.46  4846.4 2241.18  4867.2 2237.83  4886.5 2238.61  4891.7 2236.60
  4898.3 2238.33  4908.6 2238.09  4919.0 2237.55  4926.2 2235.23  4931.4 2235.63
  4960.5 2227.67  4965.9 2224.45  4981.2 2220.03  4998.4 2212.94  5005.7 2212.16
  5010.2 2210.07  5010.5 2209.57  5014.2 2210.07  5042.3 2228.01  5047.3 2228.72
  5053.4 2234.69  5063.7 2237.34  5083.8 2237.22  5088.9 2238.38  5104.9 2239.07
  5125.3 2241.56  5130.5 2241.15  5142.9 2242.92  5147.5 2243.30  5169.5 2245.63
#Mann=6,-1,0
  4837.3    0.07       0  5010.2    0.07       0  5014.2    0.07       0
  5042.3    0.16       0  5142.9    0.07       0  5147.5    0.16       0
Bank Sta=5010.2,5014.2
Exp/Cntr=0.3,0.1

Type RM Length L Ch R = 1,4322,51,51,51
BEGIN DESCRIPTION:
elmc494
END DESCRIPTION:
XS GIS Cut Line= 3
      1512950.54      6769643.35      1512898.45      6769474.07
      1512925.81      6769377.68
#Sta/Elev= 30
  4836.4 2240.71  4862.9 2239.22  4870.2 2238.09  4875.4 2236.18  4894.3 2233.61
  4915.2 2226.07  4935.6 2222.40  4940.8 2220.33  4946.6 2221.31  4951.4 2220.92
  4957.1 2220.46  4967.5 2217.88  4978.7 2211.27  4988.5 2208.12  4998.9 2208.94
  5004.2 2207.62  5004.5 2207.12  5008.0 2207.12  5008.2 2207.62  5013.5 2207.94
  5016.9 2210.91  5022.1 2213.43  5030.2 2220.38  5050.8 2231.56  5053.9 2231.85
  5056.0 2232.04  5061.4 2235.65  5071.8 2236.98  5103.0 2236.39  5113.7 2237.01
#Mann=5,-1,0
  4836.4    0.07       0  4951.4    0.16       0  5004.2    0.07       0
  5008.2    0.16       0  5053.9    0.07       0
Bank Sta=5004.2,5008.2
Exp/Cntr=0.3,0.1

Type RM Length L Ch R = 1,4271,76,76,76
BEGIN DESCRIPTION:
elmc495
END DESCRIPTION:
XS GIS Cut Line= 3
      1512997.42      6769638.17      1512951.84      6769481.89
      1512971.36      6769337.39
#Sta/Elev= 30
  4842.8 2240.25  4869.2 2238.44  4874.4 2238.88  4895.1 2237.95  4902.6 2236.72
  4915.9 2235.76  4936.1 2229.35  4941.3 2229.44  4947.1 2225.44  4950.5 2224.33
  4968.0 2219.10  4974.8 2215.47  4980.0 2214.99  4997.2 2206.05  4997.5 2205.55
  5001.0 2205.55  5001.2 2206.05  5005.0 2210.70  5010.1 2210.70  5029.7 2221.72
  5039.8 2226.55  5051.3 2229.54  5065.8 2232.20  5070.8 2228.26  5110.4 2234.34
  5130.6 2235.57  5138.4 2236.72  5143.5 2235.81  5149.8 2237.07  5151.4 2237.07
#Mann=6,-1,0
  4842.8    0.07       0  4950.5    0.16       0  4997.2    0.07       0
  5001.2    0.16       0  5051.3    0.07       0  5149.8    0.16       0
Bank Sta=4997.2,5001.2
Exp/Cntr=0.3,0.1

Type RM Length L Ch R = 1,4195,93,93,93
BEGIN DESCRIPTION:
elmc496
END DESCRIPTION:
XS GIS Cut Line= 3
      1513022.15      6769634.23      1513028.66      6769491.00
      1513065.11      6769382.96
#Sta/Elev= 30
  4853.6 2238.78  4859.8 2237.26  4869.8 2235.54  4879.9 2235.55  4889.9 2236.23
  4899.9 2236.57  4919.9 2235.87  4930.8 2233.33  4939.9 2230.02  4949.9 2225.81
  4959.9 2221.13  4980.0 2210.50  4990.0 2208.12  4996.0 2206.93  4999.1 2206.93
  5001.3 2204.42  5001.5 2203.92  5005.0 2203.92  5005.3 2204.42  5010.7 2204.94
  5021.3 2210.00  5029.5 2214.36  5042.4 2222.34  5052.9 2226.49  5061.0 2230.19
  5066.2 2231.49  5084.6 2231.86  5092.4 2232.22  5105.7 2233.24  5111.0 2233.25
#Mann=4,-1,0
  4853.6    0.07       0  4930.8    0.16       0  5001.3    0.07       0
  5005.3    0.16       0
Bank Sta=5001.3,5005.3
Exp/Cntr=0.3,0.1

Type RM Length L Ch R = 1,4102,91,91,91
BEGIN DESCRIPTION:
elmc497
END DESCRIPTION:
XS GIS Cut Line= 3
      1513037.75      6769649.90      1513110.69      6769528.76
      1513126.26      6769392.55
#Sta/Elev= 30
  4864.2 2239.05  4885.9 2236.79  4891.8 2234.83  4901.4 2232.46  4907.3 2230.42
  4913.1 2230.21  4928.7 2228.11  4936.5 2226.36  4944.5 2227.65  4950.0 2224.96
  4959.7 2224.76  4981.1 2216.41  4994.8 2207.52  5000.5 2201.44  5000.7 2200.94
  5004.2 2200.94  5004.5 2201.44  5004.9 2203.08  5008.5 2203.08  5016.4 2202.20
  5026.5 2205.61  5046.6 2211.10  5066.8 2218.50  5076.8 2220.23  5084.7 2222.88
  5089.7 2222.90  5097.0 2226.02  5117.1 2229.51  5127.1 2230.90  5142.7 2230.81
#Mann=4,-1,0
  4864.2    0.07       0  4944.5    0.16       0  5000.5    0.07       0
  5004.5    0.16       0
Bank Sta=5000.5,5004.5
Exp/Cntr=0.3,0.1

Type RM Length L Ch R = 1,4011,89,89,89
BEGIN DESCRIPTION:
elmc498
END DESCRIPTION:
XS GIS Cut Line= 3
      1513158.86      6769683.74      1513197.93      6769544.39
      1513206.91      6769421.24
#Sta/Elev= 30
  4848.1 2235.98  4850.6 2235.96  4855.8 2235.15  4874.8 2234.87  4895.6 2232.75
  4906.0 2232.61  4916.4 2231.23  4924.0 2226.77  4929.2 2226.32  4937.1 2221.74
  4950.0 2217.69  4963.3 2213.60  4968.5 2212.79  4978.7 2212.22  4988.4 2210.32
  4992.8 2210.32  4999.2 2207.37  5009.3 2204.89  5017.8 2201.23  5022.8 2201.02
  5027.3 2200.49  5027.6 2199.99  5031.1 2199.99  5031.3 2200.49  5049.4 2212.97
  5059.4 2220.18  5069.4 2225.02  5079.4 2227.16  5099.5 2229.08  5116.3 2229.94
#Mann=4,-1,0
  4848.1    0.07       0  4950.0    0.16       0  5027.3    0.07       0
  5031.3    0.16       0
Bank Sta=5027.3,5031.3
Exp/Cntr=0.3,0.1

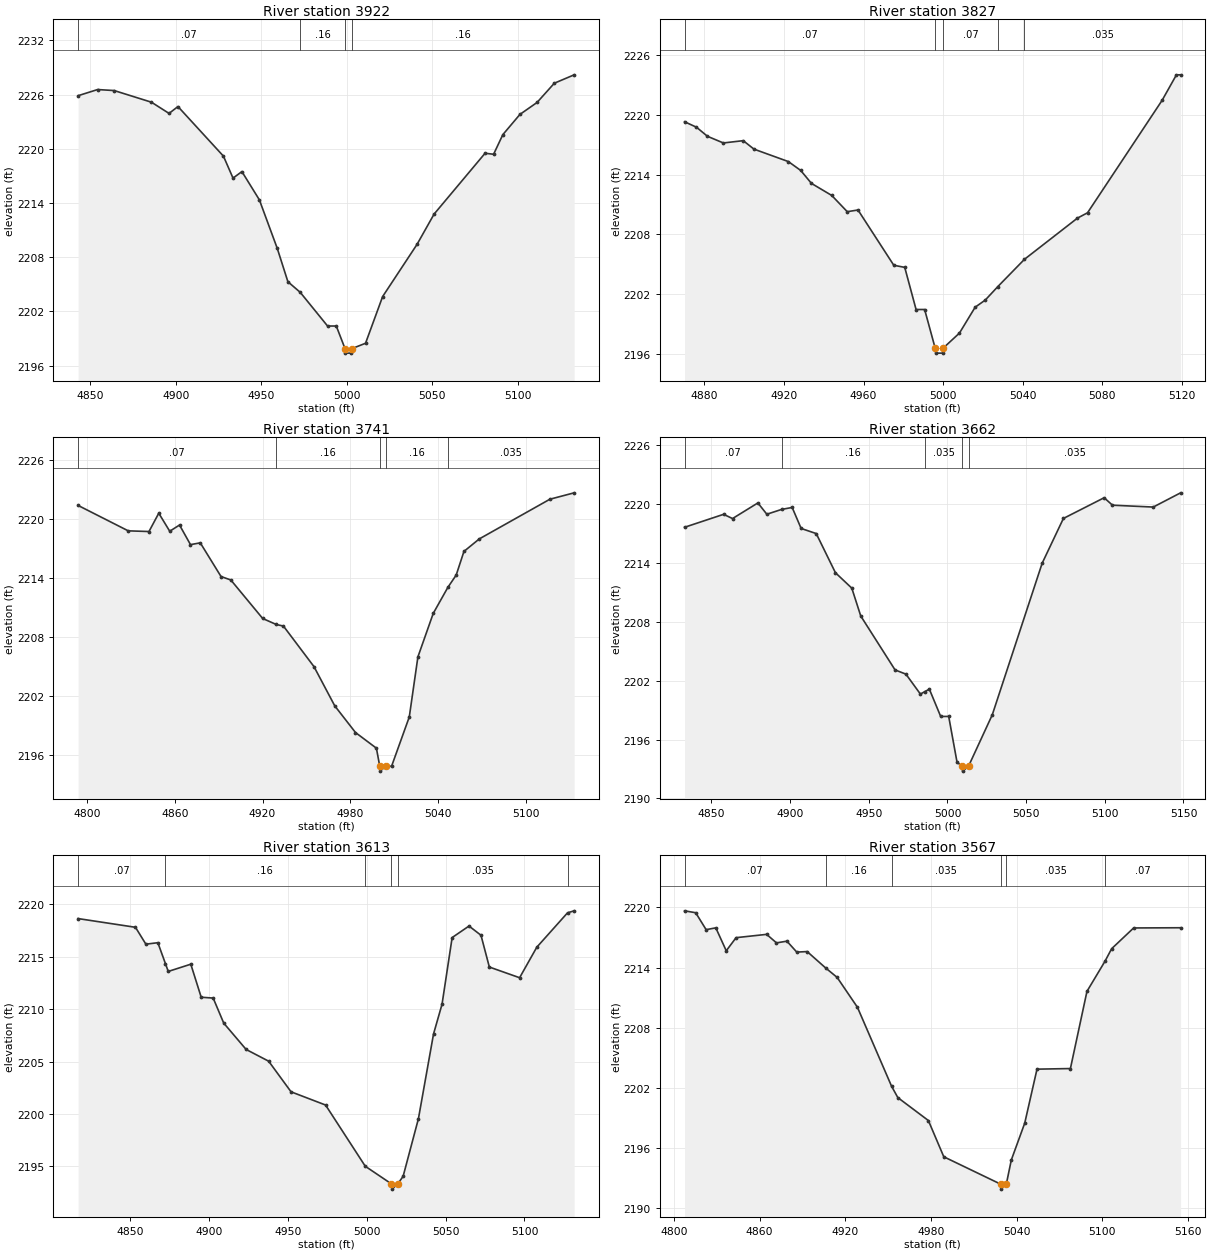
Type RM Length L Ch R = 1,3922,95,95,95
BEGIN DESCRIPTION:
elmc493
END DESCRIPTION:
XS GIS Cut Line= 3
      1513242.21      6769688.89      1513287.78      6769546.99
      1513276.06      6769406.41
#Sta/Elev= 30
  4842.9 2225.88  4854.3 2226.56  4864.0 2226.45  4885.8 2225.16  4896.1 2223.92
  4901.3 2224.68  4927.9 2219.19  4933.5 2216.76  4938.7 2217.48  4948.9 2214.36
  4959.4 2208.97  4965.6 2205.29  4972.8 2204.12  4988.8 2200.39  4993.9 2200.39
  4999.0 2197.89  4999.2 2197.39  5002.7 2197.39  5003.0 2197.89  5011.0 2198.48
  5021.0 2203.65  5041.1 2209.42  5051.1 2212.78  5080.9 2219.51  5085.9 2219.40
  5091.3 2221.57  5101.3 2223.81  5111.3 2225.13  5121.4 2227.26  5133.0 2228.19
#Mann=4,-1,0
  4842.9    0.07       0  4972.8    0.16       0  4999.0    0.07       0
  5003.0    0.16       0
Bank Sta=4999,5003
Exp/Cntr=0.3,0.1

Type RM Length L Ch R = 1,3827,86,86,86
BEGIN DESCRIPTION:
elmc492
END DESCRIPTION:
XS GIS Cut Line= 3
      1513316.42      6769705.85      1513364.60      6769595.17
      1513389.33      6769468.88
#Sta/Elev= 30
  4870.0 2219.32  4876.0 2218.77  4881.5 2217.86  4889.5 2217.19  4899.5 2217.42
  4904.9 2216.57  4922.2 2215.32  4928.4 2214.43  4933.8 2213.13  4944.0 2211.92
  4951.8 2210.29  4957.2 2210.46  4975.2 2204.91  4980.7 2204.70  4986.4 2200.47
  4990.7 2200.47  4996.0 2196.59  4996.3 2196.09  4999.8 2196.09  5000.0 2196.59
  5008.2 2198.10  5016.1 2200.70  5021.2 2201.42  5027.5 2202.77  5040.9 2205.51
  5067.5 2209.64  5072.6 2210.18  5110.1 2221.47  5117.3 2224.03  5119.4 2224.03
#Mann=5,-1,0
  4870.0    0.07       0  4996.0    0.07       0  5000.0    0.07       0
  5027.5    0.16       0  5040.9   0.035       0
Bank Sta=4996,5000
Exp/Cntr=0.3,0.1

Type RM Length L Ch R = 1,3741,79,79,79
BEGIN DESCRIPTION:
elmc491
END DESCRIPTION:
XS GIS Cut Line= 3
      1513315.11      6769746.22      1513455.74      6769587.35
      1513494.80      6769466.27
#Sta/Elev= 30
  4793.8 2221.35  4828.1 2218.77  4842.3 2218.70  4849.0 2220.56  4856.5 2218.73
  4863.2 2219.36  4870.7 2217.37  4877.4 2217.55  4891.6 2214.13  4898.3 2213.78
  4920.1 2209.87  4929.4 2209.26  4934.3 2209.10  4955.2 2204.98  4969.4 2201.00
  4983.6 2198.29  4997.9 2196.70  5000.2 2194.87  5000.5 2194.37  5004.2 2194.87
  5008.3 2194.87  5020.4 2199.87  5026.3 2205.97  5036.8 2210.39  5046.8 2213.03
  5052.5 2214.28  5057.8 2216.68  5068.3 2217.95  5116.6 2221.98  5133.2 2222.63
#Mann=5,-1,0
  4793.8    0.07       0  4929.4    0.16       0  5000.2    0.07       0
  5004.2    0.16       0  5046.8   0.035       0
Bank Sta=5000.2,5004.2
Exp/Cntr=0.3,0.1

Type RM Length L Ch R = 1,3662,49,49,49
BEGIN DESCRIPTION:
elmc489
END DESCRIPTION:
XS GIS Cut Line= 3
      1513436.20      6769781.39      1513516.94      6769634.23
      1513565.13      6769494.88
#Sta/Elev= 30
  4832.9 2217.62  4857.7 2218.94  4863.4 2218.51  4879.5 2220.10  4885.2 2218.95
  4894.6 2219.44  4901.3 2219.64  4907.0 2217.50  4916.6 2216.98  4928.8 2212.99
  4939.2 2211.42  4944.9 2208.58  4966.7 2203.09  4973.6 2202.66  4982.8 2200.63
  4985.5 2200.87  4988.5 2201.13  4995.7 2198.35  5000.8 2198.35  5006.1 2193.68
  5009.4 2193.28  5009.6 2192.78  5013.4 2193.28  5028.5 2198.52  5060.2 2213.96
  5073.7 2218.52  5099.6 2220.63  5104.9 2219.87  5130.8 2219.68  5148.2 2221.13
#Mann=5,-1,0
  4832.9    0.07       0  4894.6    0.16       0  4985.5   0.035       0
  5009.4   0.035       0  5013.4   0.035       0
Bank Sta=5009.4,5013.4
Exp/Cntr=0.3,0.1

Type RM Length L Ch R = 1,3613,46,46,46
BEGIN DESCRIPTION:
elmc490
END DESCRIPTION:
XS GIS Cut Line= 3
      1513442.75      6769786.55      1513563.82      6769647.25
      1513610.36      6769525.72
#Sta/Elev= 30
  4816.8 2218.64  4853.2 2217.81  4859.8 2216.20  4867.4 2216.34  4872.2 2214.35
  4874.0 2213.60  4888.3 2214.29  4894.9 2211.14  4902.5 2211.06  4909.2 2208.67
  4923.4 2206.16  4937.7 2205.04  4951.9 2202.12  4973.8 2200.86  4999.0 2195.02
  5015.6 2193.34  5015.9 2192.84  5019.6 2193.34  5023.0 2194.06  5032.7 2199.55
  5042.3 2207.64  5047.7 2210.48  5054.1 2216.83  5064.8 2217.93  5072.4 2217.05
  5077.7 2214.02  5096.9 2213.00  5107.8 2215.91  5127.3 2219.19  5131.5 2219.38
#Mann=6,-1,0
  4816.8    0.07       0  4872.2    0.16       0  4999.0   0.035       0
  5015.6   0.035       0  5019.6   0.035       0  5127.3    0.07       0
Bank Sta=5015.6,5019.6
Exp/Cntr=0.3,0.1

Type RM Length L Ch R = 1,3567,81,81,81
BEGIN DESCRIPTION:
elmc488
END DESCRIPTION:
XS GIS Cut Line= 3
      1513459.66      6769813.91      1513593.76      6769687.62
      1513658.87      6769537.87
#Sta/Elev= 30
  4807.4 2219.66  4815.2 2219.47  4822.5 2217.78  4829.3 2217.96  4836.6 2215.67
  4843.5 2216.98  4864.9 2217.31  4871.8 2216.46  4879.1 2216.63  4886.0 2215.54
  4893.3 2215.59  4906.2 2213.96  4914.3 2213.01  4928.5 2210.03  4952.4 2202.15
  4956.8 2201.01  4978.2 2198.72  4989.0 2195.10  5028.8 2192.37  5029.1 2191.87
  5032.8 2192.37  5036.3 2194.78  5045.7 2198.46  5054.3 2203.85  5077.7 2203.91
  5089.3 2211.62  5101.9 2214.62  5106.6 2215.88  5122.0 2217.95  5154.9 2217.97
#Mann=6,-1,0
  4807.4    0.07       0  4906.2    0.16       0  4952.4   0.035       0
  5028.8   0.035       0  5032.8   0.035       0  5101.9    0.07       0
Bank Sta=5028.8,5032.8
Exp/Cntr=0.3,0.1

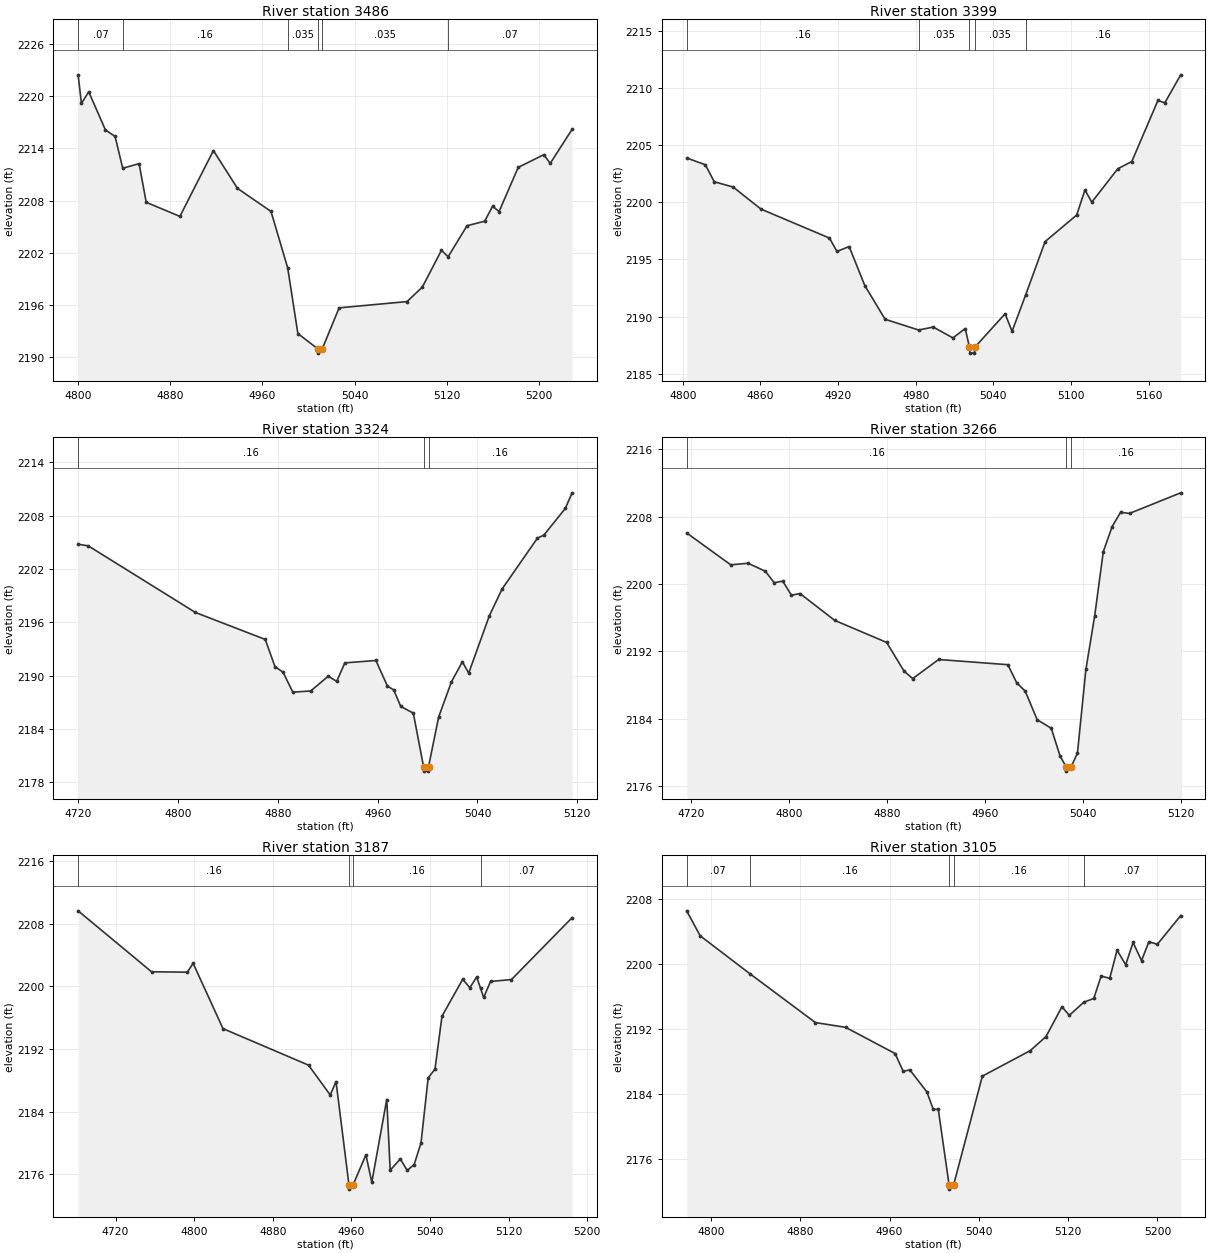
Type RM Length L Ch R = 1,3486,87,87,87
BEGIN DESCRIPTION:
elmc487
END DESCRIPTION:
XS GIS Cut Line= 3
      1513537.76      6769894.67      1513652.36      6769742.30
      1513760.88      6769530.43
#Sta/Elev= 30
  4800.0 2222.44  4802.9 2219.16  4809.2 2220.49  4823.7 2216.11  4832.1 2215.36
  4838.7 2211.71  4852.9 2212.24  4859.1 2207.80  4888.3 2206.18  4917.4 2213.74
  4938.3 2209.40  4967.4 2206.75  4981.9 2200.25  4990.7 2192.73  5007.9 2190.98
  5008.1 2190.48  5011.9 2190.98  5026.5 2195.68  5085.4 2196.40  5098.7 2198.06
  5115.3 2202.29  5121.1 2201.55  5137.5 2205.11  5152.8 2205.63  5159.7 2207.35
  5165.3 2206.74  5181.9 2211.81  5204.1 2213.27  5209.7 2212.27  5228.7 2216.19
#Mann=6,-1,0
  4800.0    0.07       0  4838.7    0.16       0  4981.9   0.035       0
  5007.9   0.035       0  5011.9   0.035       0  5121.1    0.07       0
Bank Sta=5007.9,5011.9
Exp/Cntr=0.3,0.1

Type RM Length L Ch R = 1,3399,75,75,75
BEGIN DESCRIPTION:
elmc485
END DESCRIPTION:
XS GIS Cut Line= 3
      1513643.24      6769906.37      1513742.20      6769737.09
      1513804.39      6769562.20
#Sta/Elev= 30
  4803.1 2203.87  4817.5 2203.28  4824.4 2201.79  4839.0 2201.33  4860.5 2199.40
  4913.4 2196.87  4919.2 2195.70  4928.6 2196.13  4940.7 2192.72  4956.4 2189.77
  4982.3 2188.83  4993.6 2189.09  5008.8 2188.14  5018.3 2188.96  5021.6 2187.31
  5021.9 2186.81  5025.4 2186.81  5025.6 2187.31  5049.1 2190.25  5054.5 2188.72
  5065.1 2191.93  5080.0 2196.56  5104.4 2198.88  5110.8 2201.07  5116.1 2200.01
  5136.2 2202.93  5147.0 2203.56  5167.2 2208.90  5172.5 2208.69  5184.8 2211.14
#Mann=5,-1,0
  4803.1    0.16       0  4982.3   0.035       0  5021.6   0.035       0
  5025.6   0.035       0  5065.1    0.16       0
Bank Sta=5021.6,5025.6
Exp/Cntr=0.3,0.1

Type RM Length L Ch R = 1,3324,58,58,58
BEGIN DESCRIPTION:
elmc486
END DESCRIPTION:
XS GIS Cut Line= 3
      1513647.12      6769922.02      1513796.89      6769742.30
      1513824.16      6769582.56
#Sta/Elev= 30
  4719.9 2204.79  4728.0 2204.61  4813.9 2197.11  4869.9 2194.07  4877.7 2191.01
  4884.2 2190.38  4892.0 2188.13  4906.4 2188.27  4920.4 2189.93  4927.2 2189.35
  4933.7 2191.43  4958.6 2191.70  4967.8 2188.83  4972.9 2188.38  4978.5 2186.53
  4988.6 2185.77  4996.8 2179.74  4997.0 2179.24  5000.5 2179.24  5000.8 2179.74
  5008.9 2185.33  5019.1 2189.28  5027.9 2191.55  5033.0 2190.28  5049.5 2196.72
  5059.7 2199.74  5088.1 2205.48  5093.2 2205.81  5110.4 2208.82  5115.9 2210.58
#Mann=3,-1,0
  4719.9    0.16       0  4996.8    0.07       0  5000.8    0.16       0
Bank Sta=4996.8,5000.8
Exp/Cntr=0.3,0.1

Type RM Length L Ch R = 1,3266,79,79,79
BEGIN DESCRIPTION:
elmc484
END DESCRIPTION:
XS GIS Cut Line= 3
      1513649.77      6769933.69      1513850.28      6769729.28
      1513934.92      6769648.55
#Sta/Elev= 30
  4716.4 2206.06  4752.4 2202.27  4766.5 2202.46  4780.6 2201.51  4787.8 2200.15
  4794.8 2200.33  4801.9 2198.66  4808.9 2198.86  4837.2 2195.67  4879.6 2193.05
  4893.8 2189.65  4900.9 2188.75  4922.1 2191.02  4978.6 2190.40  4985.8 2188.25
  4992.8 2187.25  5002.5 2183.86  5014.0 2182.85  5021.2 2179.55  5026.2 2178.25
  5026.4 2177.75  5030.2 2178.25  5035.4 2179.89  5042.3 2189.84  5049.5 2196.24
  5056.5 2203.84  5063.7 2206.81  5070.6 2208.52  5077.9 2208.38  5119.7 2210.83
#Mann=3,-1,0
  4716.4    0.16       0  5026.2    0.07       0  5030.2    0.16       0
Bank Sta=5026.2,5030.2
Exp/Cntr=0.3,0.1

Type RM Length L Ch R = 1,3187,82,82,82
BEGIN DESCRIPTION:
elmc483
END DESCRIPTION:
XS GIS Cut Line= 3
      1513627.61      6769963.66      1513895.85      6769791.78
      1514027.26      6769662.97
#Sta/Elev= 30
  4681.9 2209.64  4756.6 2201.86  4793.0 2201.81  4798.9 2202.94  4829.3 2194.60
  4916.3 2189.94  4938.4 2186.13  4944.3 2187.84  4957.5 2174.61  4957.8 2174.11
  4961.5 2174.61  4974.7 2178.49  4980.7 2174.99  4995.9 2185.55  4999.4 2176.52
  5009.7 2177.97  5016.7 2176.50  5023.8 2177.25  5030.8 2180.04  5038.0 2188.29
  5045.0 2189.45  5052.1 2196.19  5073.2 2200.91  5080.4 2199.82  5087.4 2201.19
  5091.3 2199.76  5094.5 2198.58  5101.5 2200.62  5122.8 2200.87  5184.5 2208.77
#Mann=4,-1,0
  4681.9    0.16       0  4957.5    0.07       0  4961.5    0.16       0
  5091.3    0.07       0
Bank Sta=4957.5,4961.5
Exp/Cntr=0.3,0.1

Type RM Length L Ch R = 1,3105,53,53,53
BEGIN DESCRIPTION:
elmc482
END DESCRIPTION:
XS GIS Cut Line= 3
      1513687.53      6769977.97      1513877.62      6769856.89
      1514019.20      6769692.14
#Sta/Elev= 30
  4778.3 2206.53  4790.3 2203.46  4834.8 2198.79  4893.6 2192.76  4920.7 2192.17
  4965.0 2188.94  4972.3 2186.75  4978.2 2186.93  4993.5 2184.21  4999.2 2182.06
  5003.7 2182.06  5013.4 2172.73  5013.6 2172.23  5017.4 2172.73  5043.2 2186.16
  5086.0 2189.29  5100.2 2191.03  5114.5 2194.71  5121.1 2193.65  5134.1 2195.27
  5143.0 2195.73  5149.6 2198.49  5157.3 2198.21  5163.9 2201.68  5171.6 2199.88
  5178.2 2202.63  5185.8 2200.40  5192.4 2202.72  5200.0 2202.41  5220.9 2205.94
#Mann=5,-1,0
  4778.3    0.07       0  4834.8    0.16       0  5013.4    0.07       0
  5017.4    0.16       0  5134.1    0.07       0
Bank Sta=5013.4,5017.4
Exp/Cntr=0.3,0.1

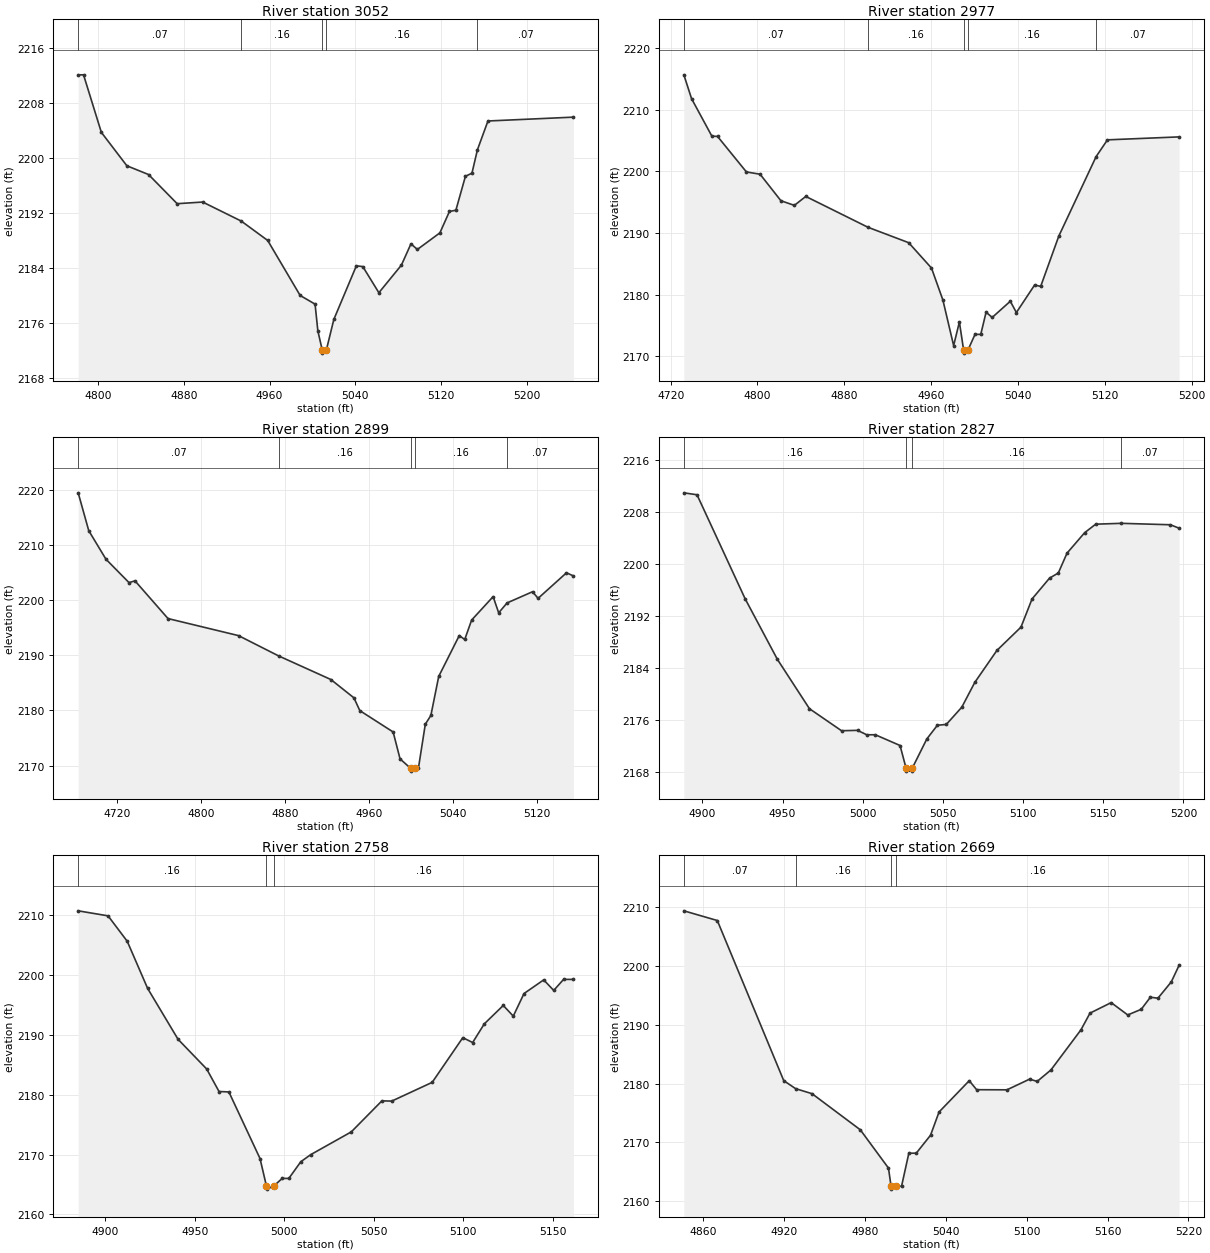
Type RM Length L Ch R = 1,3052,75,75,75
BEGIN DESCRIPTION:
elmc480
END DESCRIPTION:
XS GIS Cut Line= 3
      1513886.74      6770102.94      1513917.98      6769884.23
      1514053.39      6769685.03
#Sta/Elev= 30
  4781.5 2212.13  4786.5 2212.13  4803.1 2203.77  4826.9 2198.91  4847.1 2197.64
  4873.8 2193.40  4897.6 2193.64  4933.6 2190.87  4958.2 2188.06  4988.5 2180.06
  5002.4 2178.80  5005.0 2174.91  5009.0 2172.18  5009.3 2171.68  5013.0 2172.18
  5019.9 2176.58  5040.9 2184.37  5046.9 2184.26  5061.9 2180.46  5082.9 2184.47
  5091.8 2187.56  5097.8 2186.75  5118.8 2189.16  5127.7 2192.27  5133.7 2192.45
  5142.6 2197.38  5148.7 2197.84  5153.8 2201.24  5163.6 2205.42  5243.3 2205.98
#Mann=5,-1,0
  4781.5    0.07       0  4933.6    0.16       0  5009.0    0.07       0
  5013.0    0.16       0  5153.8    0.07       0
Bank Sta=5009,5013
Exp/Cntr=0.3,0.1

Type RM Length L Ch R = 1,2977,78,78,78
BEGIN DESCRIPTION:
elmc481
END DESCRIPTION:
XS GIS Cut Line= 3
      1513901.05      6770114.72      1513985.69      6769856.89
      1514068.35      6769691.58
#Sta/Elev= 30
  4732.2 2215.63  4739.3 2211.76  4758.0 2205.69  4763.2 2205.65  4789.8 2199.89
  4802.4 2199.52  4821.6 2195.22  4834.0 2194.47  4844.5 2195.92  4901.8 2190.92
  4939.3 2188.42  4960.3 2184.31  4970.8 2179.13  4980.7 2171.74  4986.0 2175.57
  4989.9 2171.02  4990.1 2170.52  4993.9 2171.02  5000.4 2173.56  5005.7 2173.56
  5010.6 2177.16  5016.2 2176.30  5032.9 2178.93  5038.5 2177.10  5055.3 2181.56
  5060.9 2181.34  5077.6 2189.50  5112.0 2202.39  5122.4 2205.09  5188.4 2205.57
#Mann=5,-1,0
  4732.2    0.07       0  4901.8    0.16       0  4989.9    0.07       0
  4993.9    0.16       0  5112.0    0.07       0
Bank Sta=4989.9,4993.9
Exp/Cntr=0.3,0.1

Type RM Length L Ch R = 1,2899,72,72,72
BEGIN DESCRIPTION:
elmc479
END DESCRIPTION:
XS GIS Cut Line= 3
      1513906.26      6770123.83      1514056.00      6769839.96
      1514101.58      6769695.42
#Sta/Elev= 30
  4682.5 2219.40  4692.6 2212.54  4709.0 2207.38  4731.0 2203.14  4736.7 2203.46
  4768.2 2196.63  4835.5 2193.54  4873.7 2189.87  4923.6 2185.59  4945.6 2182.27
  4951.2 2179.96  4983.0 2176.09  4989.6 2171.22  4999.7 2169.50  5000.0 2169.00
  5003.7 2169.50  5007.1 2169.50  5013.7 2177.50  5019.0 2179.08  5026.5 2186.16
  5046.1 2193.55  5051.3 2192.84  5057.9 2196.36  5078.4 2200.60  5083.7 2197.67
  5091.7 2199.46  5116.0 2201.49  5121.3 2200.29  5148.4 2204.92  5155.0 2204.35
#Mann=5,-1,0
  4682.5    0.07       0  4873.7    0.16       0  4999.7    0.07       0
  5003.7    0.16       0  5091.7    0.07       0
Bank Sta=4999.7,5003.7
Exp/Cntr=0.3,0.1

Type RM Length L Ch R = 1,2827,69,69,69
BEGIN DESCRIPTION:
elmc478
END DESCRIPTION:
XS GIS Cut Line= 3
      1514106.79      6769996.21      1514111.99      6769881.63
      1514190.47      6769704.10
#Sta/Elev= 30
  4888.5 2210.92  4896.7 2210.62  4926.7 2194.63  4946.8 2185.32  4966.8 2177.73
  4986.8 2174.34  4996.8 2174.40  5002.5 2173.72  5007.9 2173.72  5023.3 2172.07
  5027.0 2168.63  5027.3 2168.13  5030.8 2168.13  5031.0 2168.63  5040.0 2173.08
  5046.6 2175.19  5052.1 2175.30  5061.8 2177.96  5069.9 2181.77  5083.7 2186.69
  5098.7 2190.27  5105.6 2194.60  5116.5 2197.80  5122.0 2198.60  5127.4 2201.64
  5138.4 2204.79  5145.3 2206.10  5161.3 2206.23  5191.9 2206.01  5197.3 2205.48
#Mann=4,-1,0
  4888.5    0.16       0  5027.0    0.07       0  5031.0    0.16       0
  5161.3    0.07       0
Bank Sta=5027,5031
Exp/Cntr=0.3,0.1

Type RM Length L Ch R = 1,2758,89,89,89
BEGIN DESCRIPTION:
elmc477
END DESCRIPTION:
XS GIS Cut Line= 3
      1514126.31      6770013.16      1514175.80      6769906.37
      1514244.81      6769763.13
#Sta/Elev= 30
  4884.8 2210.69  4901.5 2209.85  4912.2 2205.61  4923.6 2197.74  4940.6 2189.24
  4956.6 2184.28  4963.5 2180.52  4969.0 2180.45  4986.4 2169.33  4990.0 2164.72
  4990.2 2164.22  4994.0 2164.72  4998.8 2166.01  5002.5 2166.01  5009.2 2168.80
  5014.8 2169.99  5037.4 2173.78  5054.5 2178.96  5060.0 2178.92  5082.6 2182.05
  5099.7 2189.51  5105.2 2188.70  5111.7 2191.81  5122.3 2194.89  5127.9 2193.11
  5133.9 2196.88  5144.9 2199.16  5150.5 2197.40  5156.0 2199.24  5161.5 2199.24
#Mann=3,-1,0
  4884.8    0.16       0  4990.0    0.07       0  4994.0    0.16       0
Bank Sta=4990,4994
Exp/Cntr=0.3,0.1

Type RM Length L Ch R = 1,2669,55,55,55
BEGIN DESCRIPTION:
elmc476
END DESCRIPTION:
XS GIS Cut Line= 3
      1514149.73      6770057.43      1514255.22      6769941.52
      1514348.92      6769752.83
#Sta/Elev= 30
  4845.7 2209.43  4870.5 2207.78  4919.8 2180.51  4928.6 2179.15  4940.8 2178.29
  4976.6 2172.14  4997.5 2165.62  4999.4 2162.54  4999.7 2162.04  5003.4 2162.54
  5007.2 2162.54  5012.6 2168.16  5018.1 2168.16  5028.7 2171.22  5035.0 2175.17
  5057.4 2180.50  5062.9 2178.97  5085.4 2178.95  5102.2 2180.77  5107.8 2180.38
  5118.0 2182.33  5140.3 2189.17  5147.0 2192.01  5162.7 2193.80  5175.0 2191.70
  5185.0 2192.66  5191.8 2194.72  5197.4 2194.55  5207.3 2197.33  5213.1 2200.16
#Mann=4,-1,0
  4845.7    0.07       0  4928.6    0.16       0  4999.4    0.07       0
  5003.4    0.16       0
Bank Sta=4999.4,5003.4
Exp/Cntr=0.3,0.1

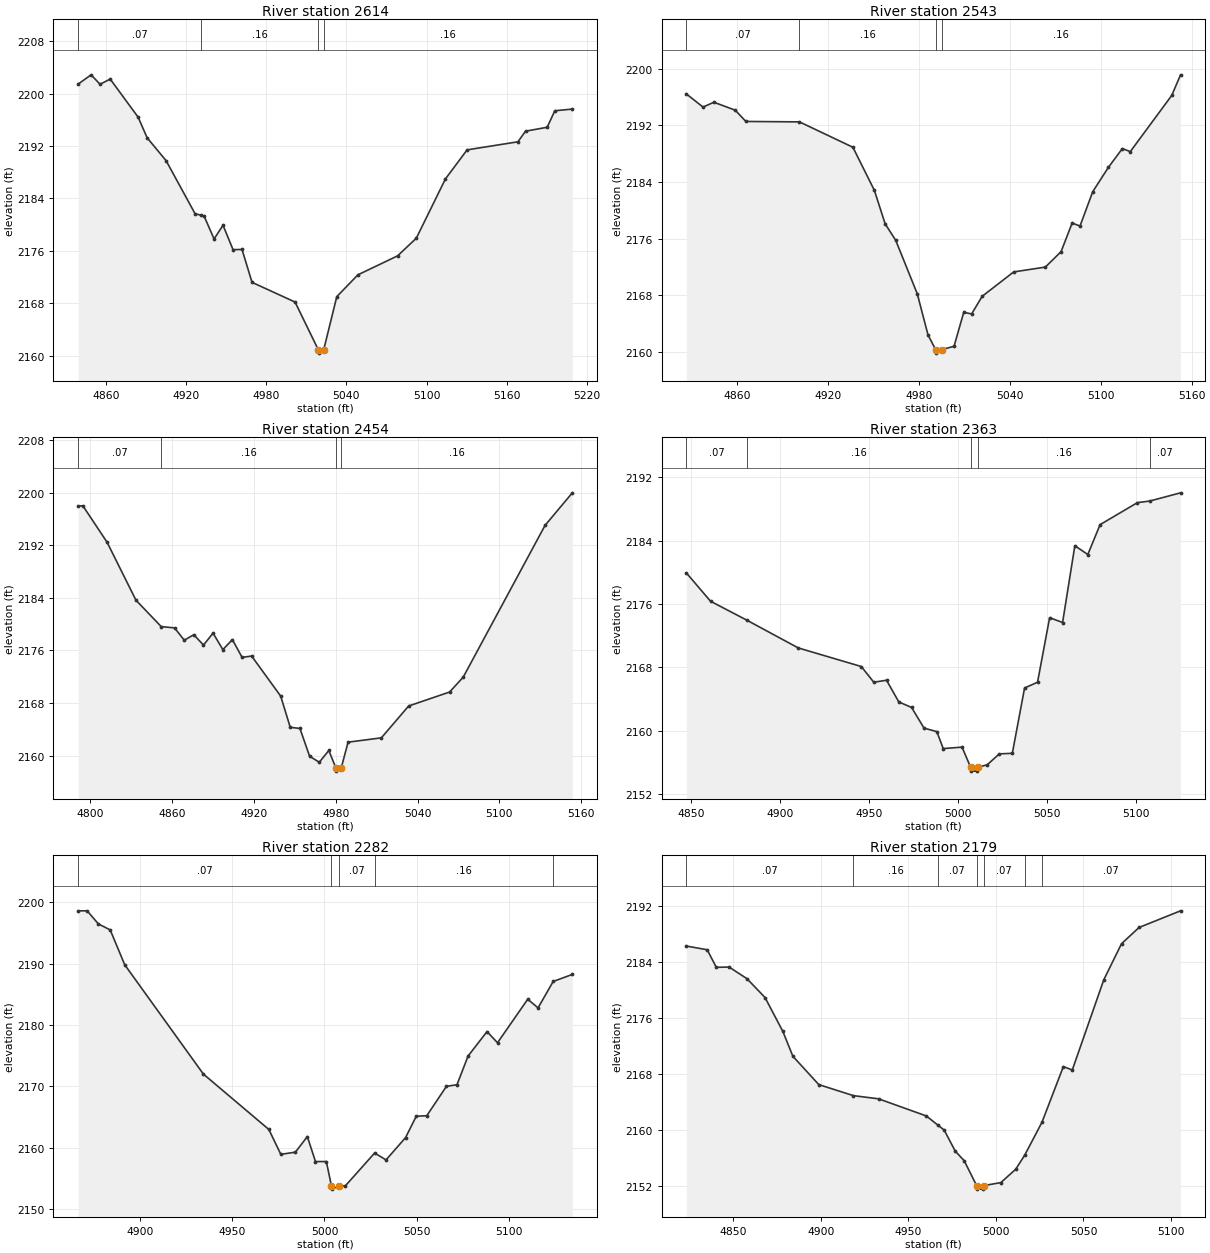
Type RM Length L Ch R = 1,2614,71,71,71
BEGIN DESCRIPTION:
elmc475
END DESCRIPTION:
XS GIS Cut Line= 3
      1514190.12      6770096.47      1514298.19      6769975.38
      1514397.14      6769793.11
#Sta/Elev= 30
  4839.3 2201.47  4849.0 2202.89  4855.7 2201.45  4863.3 2202.24  4884.2 2196.42
  4890.9 2193.28  4905.1 2189.78  4926.8 2181.67  4931.2 2181.45  4933.5 2181.33
  4941.0 2177.82  4947.7 2179.91  4955.2 2176.18  4961.9 2176.22  4969.4 2171.19
  5001.6 2168.18  5019.0 2160.88  5019.3 2160.38  5023.0 2160.88  5032.8 2169.01
  5048.6 2172.34  5078.3 2175.24  5092.3 2177.94  5114.1 2187.00  5130.3 2191.43
  5168.3 2192.66  5174.0 2194.28  5190.2 2194.88  5195.9 2197.40  5209.0 2197.66
#Mann=4,-1,0
  4839.3    0.07       0  4931.2    0.16       0  5019.0    0.07       0
  5023.0    0.16       0
Bank Sta=5019,5023
Exp/Cntr=0.3,0.1

Type RM Length L Ch R = 1,2543,89,89,89
BEGIN DESCRIPTION:
elmc474
END DESCRIPTION:
XS GIS Cut Line= 3
      1514243.49      6770112.11      1514367.20      6769985.79
      1514409.83      6769842.40
#Sta/Elev= 30
  4826.3 2196.43  4837.3 2194.57  4844.5 2195.25  4858.6 2194.13  4865.6 2192.54
  4901.0 2192.48  4936.3 2188.90  4950.5 2182.81  4957.6 2178.09  4964.6 2175.76
  4978.8 2168.23  4985.9 2162.43  4990.9 2160.35  4991.2 2159.85  4994.9 2160.35
  5003.1 2160.81  5009.5 2165.61  5014.7 2165.38  5021.7 2167.87  5042.5 2171.31
  5063.4 2171.99  5073.8 2174.17  5081.1 2178.21  5086.3 2177.78  5094.7 2182.63
  5105.1 2186.08  5114.3 2188.72  5119.5 2188.28  5146.9 2196.22  5152.7 2199.12
#Mann=4,-1,0
  4826.3    0.07       0  4901.0    0.16       0  4990.9    0.07       0
  4994.9    0.16       0
Bank Sta=4990.9,4994.9
Exp/Cntr=0.3,0.1

Type RM Length L Ch R = 1,2454,91,91,91
BEGIN DESCRIPTION:
elmc392
END DESCRIPTION:
XS GIS Cut Line= 3
      1514305.00      6770138.00      1514453.75      6769991.46
      1514455.00      6769837.96
#Sta/Elev= 30
  4791.2 2197.98  4794.7 2197.98  4812.4 2192.46  4833.6 2183.64  4852.1 2179.63
  4861.9 2179.43  4869.0 2177.56  4876.0 2178.39  4883.1 2176.82  4890.1 2178.63
  4897.3 2176.13  4904.3 2177.65  4911.4 2174.95  4918.4 2175.15  4939.7 2169.06
  4946.7 2164.32  4953.8 2164.15  4960.9 2159.92  4968.0 2159.01  4975.0 2160.80
  4980.1 2158.16  4980.4 2157.66  4984.1 2158.16  4989.1 2162.06  5013.5 2162.72
  5033.5 2167.56  5063.5 2169.68  5073.5 2171.94  5133.5 2195.01  5153.5 2199.96
#Mann=4,-1,0
  4791.2    0.07       0  4852.1    0.16       0  4980.1    0.07       0
  4984.1    0.16       0
Bank Sta=4980.1,4984.1
Exp/Cntr=0.3,0.1

Type RM Length L Ch R = 1,2363,81,81,81
BEGIN DESCRIPTION:
elmc473
END DESCRIPTION:
XS GIS Cut Line= 3
      1514399.76      6770171.98      1514500.01      6770067.82
      1514591.24      6769970.17
#Sta/Elev= 30
  4847.1 2179.95  4860.7 2176.37  4881.2 2173.97  4910.1 2170.47  4945.6 2168.12
  4952.6 2166.14  4959.8 2166.39  4966.7 2163.65  4973.9 2162.95  4980.9 2160.34
  4988.1 2159.90  4991.7 2157.76  5002.3 2157.94  5007.1 2155.41  5007.4 2154.91
  5010.9 2154.91  5011.1 2155.41  5016.4 2155.70  5023.3 2157.09  5030.6 2157.16
  5037.5 2165.41  5044.8 2166.14  5051.6 2174.29  5058.9 2173.68  5065.8 2183.38
  5073.1 2182.27  5080.0 2186.04  5101.0 2188.82  5107.9 2189.02  5125.3 2190.06
#Mann=5,-1,0
  4847.1    0.07       0  4881.2    0.16       0  5007.1    0.07       0
  5011.1    0.16       0  5107.9    0.07       0
Bank Sta=5007.1,5011.1
Exp/Cntr=0.3,0.1

Type RM Length L Ch R = 1,2282,103,103,103
BEGIN DESCRIPTION:
elmc472
END DESCRIPTION:
XS GIS Cut Line= 3
      1514462.28      6770230.55      1514545.59      6770129.02
      1514609.39      6770007.93
#Sta/Elev= 30
  4866.3 2198.64  4871.2 2198.64  4877.3 2196.50  4883.7 2195.53  4891.6 2189.83
  4934.3 2171.99  4969.8 2162.96  4976.3 2158.90  4984.2 2159.25  4990.7 2161.80
  4995.1 2157.72  5001.0 2157.72  5003.8 2153.72  5004.0 2153.22  5007.8 2153.72
  5011.4 2153.78  5027.2 2159.11  5033.4 2157.99  5044.0 2161.63  5049.8 2165.12
  5055.5 2165.20  5066.2 2170.00  5071.9 2170.25  5077.9 2174.93  5088.2 2178.93
  5093.9 2177.11  5110.3 2184.21  5115.9 2182.80  5124.1 2187.11  5134.5 2188.26
#Mann=5,-1,0
  4866.3    0.07       0  5003.8    0.07       0  5007.8    0.07       0
  5027.2    0.16       0  5124.1    0.07       0
Bank Sta=5003.8,5007.8
Exp/Cntr=0.3,0.1

Type RM Length L Ch R = 1,2179,106,106,106
BEGIN DESCRIPTION:
elmc471
END DESCRIPTION:
XS GIS Cut Line= 3
      1514673.19      6770261.82      1514635.43      6770089.96
      1514647.15      6769984.47
#Sta/Elev= 30
  4823.3 2186.31  4835.2 2185.78  4840.4 2183.27  4847.7 2183.31  4857.9 2181.65
  4868.2 2178.96  4878.4 2174.11  4884.1 2170.57  4898.9 2166.52  4918.7 2164.94
  4933.0 2164.49  4960.3 2162.04  4966.9 2160.73  4970.5 2160.02  4976.8 2157.01
  4981.9 2155.65  4989.0 2152.09  4989.3 2151.59  4992.8 2151.59  4993.0 2152.09
  5002.8 2152.52  5011.3 2154.43  5016.4 2156.42  5026.3 2161.14  5038.5 2169.09
  5043.6 2168.61  5061.6 2181.50  5071.7 2186.64  5081.7 2188.96  5105.4 2191.34
#Mann=7,-1,0
  4823.3    0.07       0  4918.7    0.16       0  4966.9    0.07       0
  4989.0    0.07       0  4993.0    0.07       0  5016.4    0.16       0
  5026.3    0.07       0
Bank Sta=4989,4993
Exp/Cntr=0.3,0.1