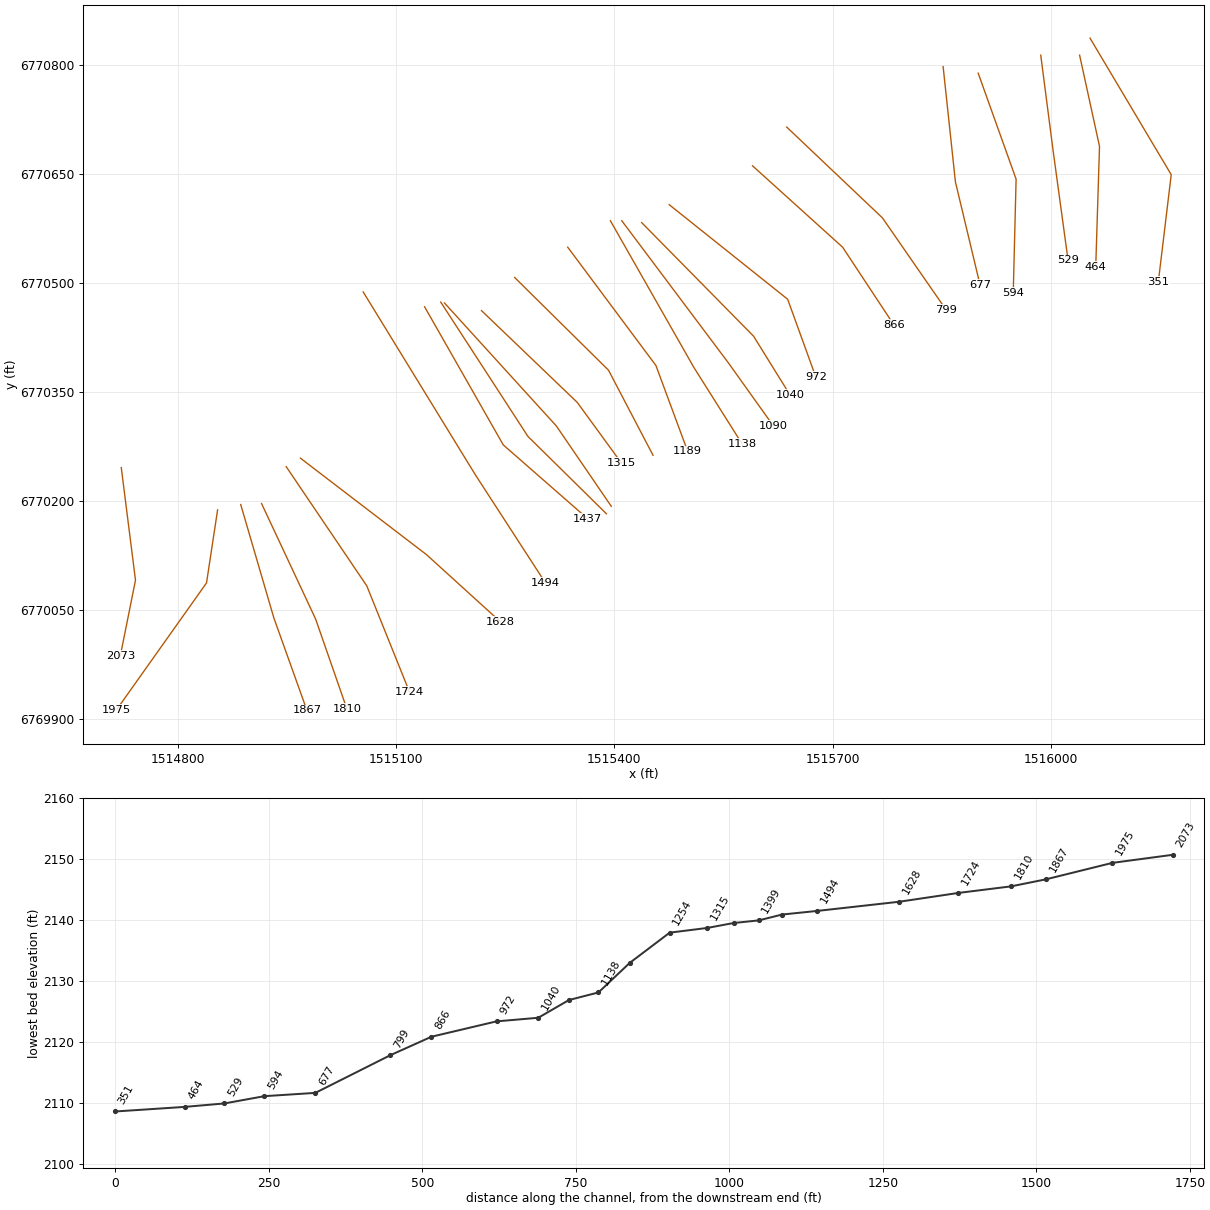
HEC-RAS study Elm 55.prj: Elm 55 Base Level Engineering

--- Elm 55.g01 (geometry) --- (continued)

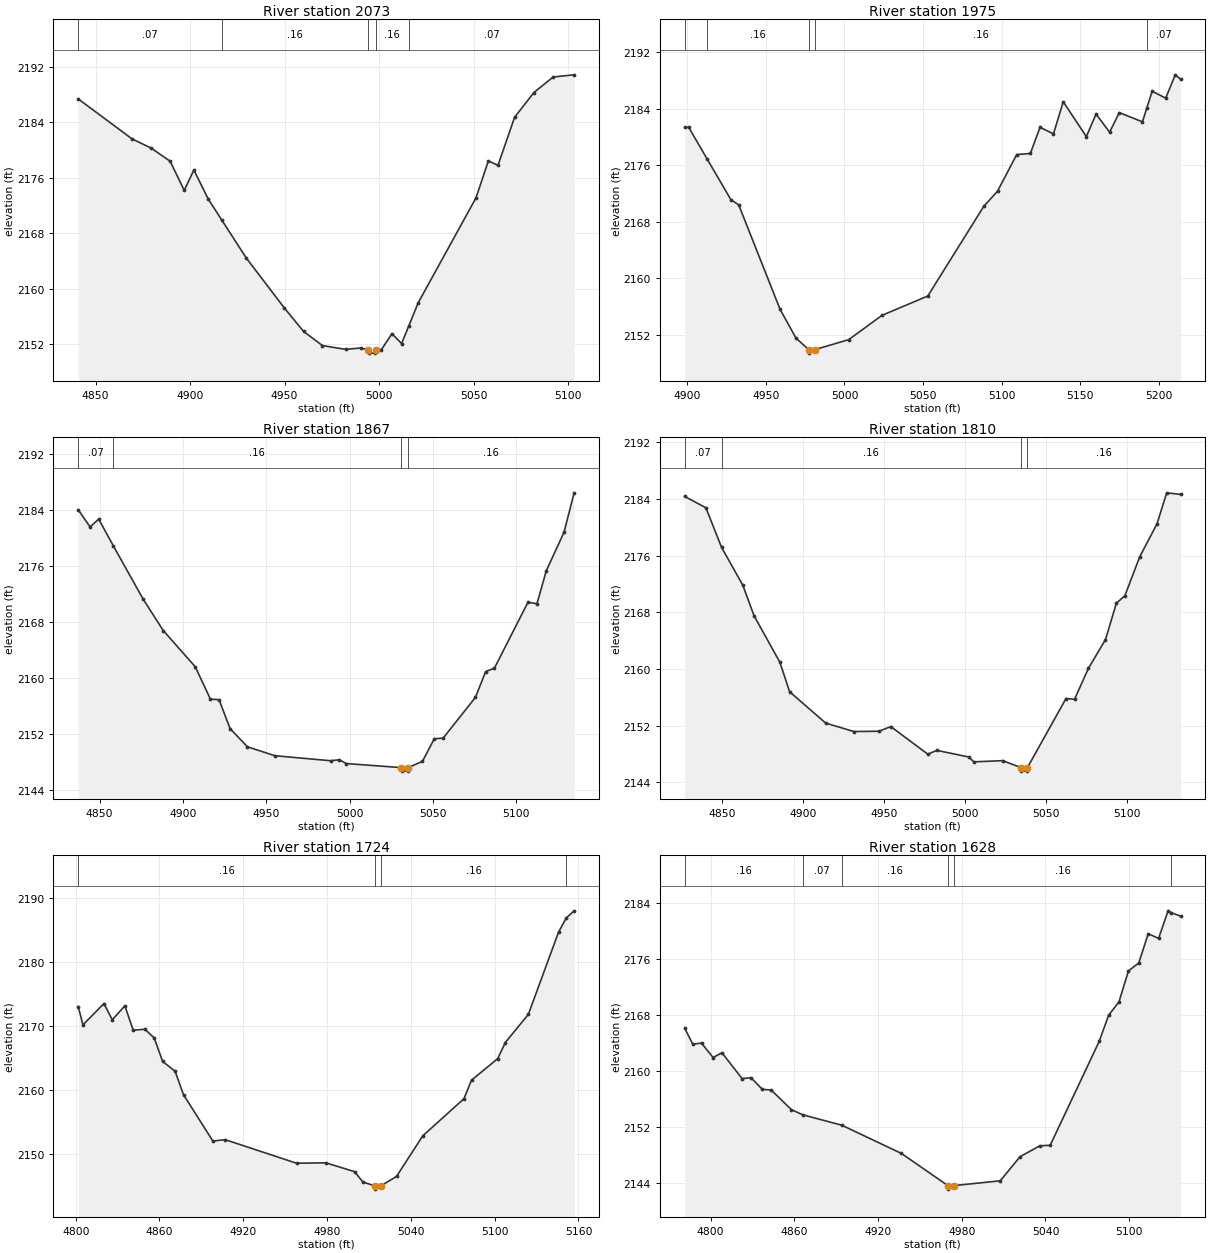
Type RM Length L Ch R = 1,2073,98,98,98
BEGIN DESCRIPTION:
elmc470
END DESCRIPTION:
XS GIS Cut Line= 3
      1514722.67      6770246.23      1514742.20      6770091.26
      1514721.37      6769987.12
#Sta/Elev= 30
  4840.8 2187.36  4869.3 2181.60  4879.3 2180.29  4889.4 2178.40  4896.9 2174.19
  4902.0 2177.12  4909.6 2172.94  4916.8 2169.90  4929.7 2164.46  4949.9 2157.24
  4960.0 2153.89  4970.0 2151.84  4982.3 2151.29  4990.2 2151.49  4994.1 2151.25
  4994.4 2150.75  4997.9 2150.75  4998.1 2151.25  5001.2 2151.25  5006.8 2153.55
  5011.9 2152.13  5015.6 2154.60  5020.7 2158.01  5051.3 2173.13  5057.8 2178.43
  5062.9 2177.80  5071.7 2184.72  5081.9 2188.28  5092.1 2190.52  5103.2 2190.83
#Mann=5,-1,0
  4840.8    0.07       0  4916.8    0.16       0  4994.1    0.07       0
  4998.1    0.16       0  5015.6    0.07       0
Bank Sta=4994.1,4998.1
Exp/Cntr=0.3,0.1

Type RM Length L Ch R = 1,1975,108,108,108
BEGIN DESCRIPTION:
elmc391
END DESCRIPTION:
XS GIS Cut Line= 3
      1514855.00      6770188.03      1514839.78      6770087.48
      1514716.18      6769912.90
#Sta/Elev= 30
  4898.3 2181.37  4900.9 2181.37  4912.4 2176.97  4927.7 2171.15  4932.7 2170.40
  4959.0 2155.63  4969.1 2151.57  4977.2 2149.93  4977.5 2149.43  4981.2 2149.93
  5002.7 2151.34  5023.9 2154.78  5053.0 2157.51  5088.7 2170.22  5097.4 2172.35
  5109.6 2177.53  5118.3 2177.68  5124.4 2181.38  5133.0 2180.46  5139.2 2185.00
  5153.9 2180.07  5160.1 2183.26  5168.7 2180.69  5174.9 2183.46  5189.6 2182.16
  5192.4 2184.12  5195.8 2186.49  5204.4 2185.51  5210.5 2188.81  5213.9 2188.18
#Mann=5,-1,0
  4898.3    0.07       0  4912.4    0.16       0  4977.2    0.07       0
  4981.2    0.16       0  5192.4    0.07       0
Bank Sta=4977.2,4981.2
Exp/Cntr=0.3,0.1

Type RM Length L Ch R = 1,1867,57,57,57
BEGIN DESCRIPTION:
elmc469
END DESCRIPTION:
XS GIS Cut Line= 3
      1514886.74      6770195.41      1514932.31      6770039.18
      1514977.63      6769912.27
#Sta/Elev= 30
  4837.2 2183.99  4844.3 2181.54  4849.5 2182.65  4858.2 2178.87  4876.2 2171.23
  4888.2 2166.78  4907.4 2161.62  4916.5 2157.00  4921.7 2156.92  4928.3 2152.80
  4938.7 2150.21  4955.1 2148.94  4988.6 2148.22  4993.8 2148.36  4998.0 2147.82
  5031.1 2147.24  5031.3 2146.74  5034.8 2146.74  5035.1 2147.24  5043.7 2148.13
  5050.8 2151.35  5056.1 2151.44  5075.5 2157.26  5081.6 2160.92  5086.9 2161.43
  5107.0 2170.81  5112.4 2170.60  5118.0 2175.30  5128.6 2180.76  5134.7 2186.40
#Mann=4,-1,0
  4837.2    0.07       0  4858.2    0.16       0  5031.1    0.07       0
  5035.1    0.16       0
Bank Sta=5031.1,5035.1
Exp/Cntr=0.3,0.1

Type RM Length L Ch R = 1,1810,86,86,86
BEGIN DESCRIPTION:
elmc468
END DESCRIPTION:
XS GIS Cut Line= 3
      1514915.37      6770196.75      1514989.60      6770037.88
      1515032.56      6769914.18
#Sta/Elev= 30
  4826.7 2184.36  4839.8 2182.76  4849.5 2177.16  4862.6 2171.83  4869.5 2167.54
  4885.5 2160.95  4891.5 2156.79  4913.8 2152.36  4931.2 2151.17  4946.7 2151.21
  4954.0 2151.87  4976.9 2147.97  4982.4 2148.51  5002.1 2147.58  5005.3 2146.89
  5023.1 2147.06  5034.4 2146.08  5034.6 2145.58  5038.1 2145.58  5038.4 2146.08
  5062.2 2155.83  5067.5 2155.72  5076.0 2160.07  5086.6 2164.15  5093.3 2169.27
  5098.6 2170.36  5107.8 2175.87  5118.4 2180.48  5124.4 2184.87  5133.0 2184.65
#Mann=4,-1,0
  4826.7    0.07       0  4849.5    0.16       0  5034.4    0.07       0
  5038.4    0.16       0
Bank Sta=5034.4,5038.4
Exp/Cntr=0.3,0.1

Type RM Length L Ch R = 1,1724,96,96,96
BEGIN DESCRIPTION:
elmc467
END DESCRIPTION:
XS GIS Cut Line= 3
      1514949.22      6770247.53      1515059.91      6770083.45
      1515118.51      6769937.61
#Sta/Elev= 30
  4801.8 2173.05  4805.2 2170.18  4820.2 2173.51  4826.2 2170.98  4835.2 2173.16
  4841.2 2169.34  4849.5 2169.50  4856.2 2168.14  4862.2 2164.49  4871.2 2162.91
  4877.2 2159.26  4898.2 2152.02  4907.1 2152.23  4958.1 2148.55  4979.1 2148.61
  4999.7 2147.23  5005.6 2145.61  5014.4 2145.00  5014.6 2144.50  5018.4 2145.00
  5029.7 2146.48  5048.5 2152.83  5078.0 2158.64  5083.4 2161.53  5102.2 2164.91
  5107.6 2167.42  5124.1 2171.82  5145.7 2184.66  5151.2 2186.88  5156.9 2188.01
#Mann=4,-1,0
  4801.8    0.16       0  5014.4    0.07       0  5018.4    0.16       0
  5151.2    0.07       0
Bank Sta=5014.4,5018.4
Exp/Cntr=0.3,0.1

Type RM Length L Ch R = 1,1628,134,134,134
BEGIN DESCRIPTION:
elmc466
END DESCRIPTION:
XS GIS Cut Line= 3
      1514968.80      6770259.20      1515141.94      6770126.42
      1515243.48      6770033.99
#Sta/Elev= 30
  4781.4 2166.12  4787.2 2163.84  4793.5 2163.97  4801.8 2161.91  4808.1 2162.60
  4822.6 2158.89  4828.9 2159.03  4837.1 2157.35  4843.4 2157.26  4857.9 2154.45
  4865.9 2153.72  4894.0 2152.22  4936.8 2148.17  4970.1 2143.56  4970.4 2143.06
  4974.1 2143.56  5007.6 2144.25  5021.8 2147.71  5036.0 2149.27  5043.4 2149.34
  5078.5 2164.21  5085.3 2167.98  5092.7 2169.88  5099.5 2174.32  5106.9 2175.46
  5113.7 2179.65  5121.1 2178.98  5127.9 2182.93  5130.2 2182.67  5136.9 2182.17
#Mann=6,-1,0
  4781.4    0.16       0  4865.9    0.07       0  4894.0    0.16       0
  4970.1    0.07       0  4974.1    0.16       0  5130.2    0.07       0
Bank Sta=4970.1,4974.1
Exp/Cntr=0.3,0.1

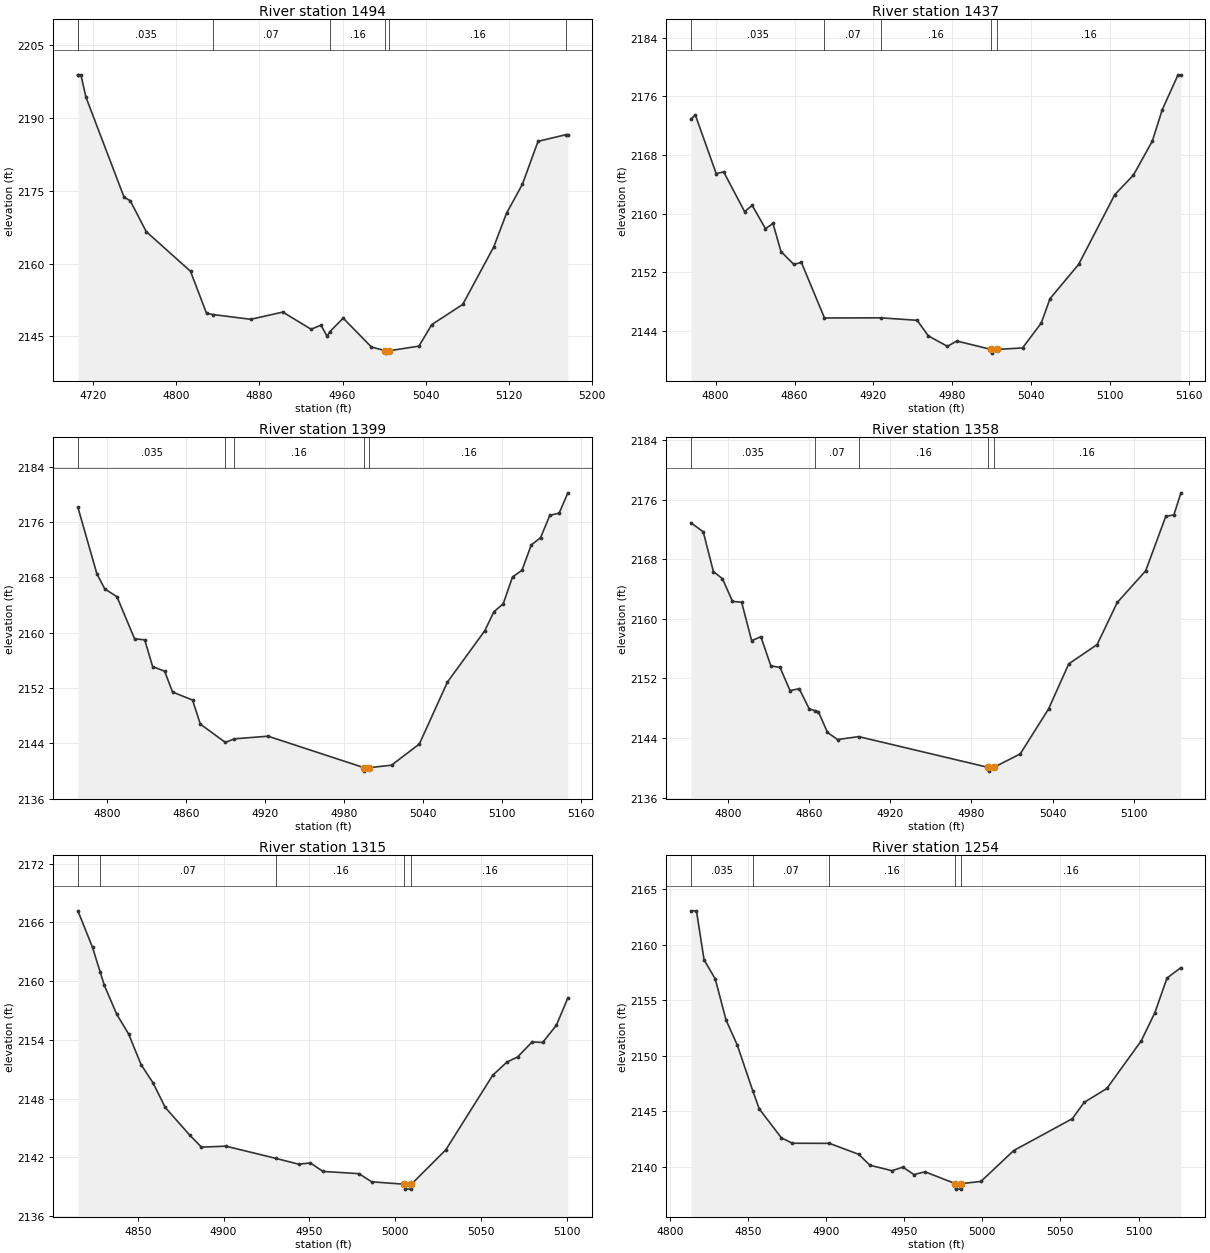
Type RM Length L Ch R = 1,1494,57,57,57
BEGIN DESCRIPTION:
elmc390
END DESCRIPTION:
XS GIS Cut Line= 3
      1515054.99      6770488.01      1515208.89      6770236.57
      1515304.98      6770088.04
#Sta/Elev= 30
  4705.2 2198.90  4705.7 2198.90  4708.1 2198.90  4712.9 2194.32  4749.7 2173.65
  4755.5 2172.98  4771.0 2166.59  4813.6 2158.42  4829.0 2149.77  4834.9 2149.51
  4871.6 2148.52  4902.5 2150.01  4929.7 2146.47  4939.2 2147.31  4945.1 2145.03
  4947.8 2145.99  4960.6 2148.76  4987.7 2142.83  5001.1 2142.05  5001.4 2141.55
  5005.1 2142.05  5033.5 2142.99  5045.9 2147.43  5075.7 2151.59  5105.5 2163.42
  5117.9 2170.40  5133.1 2176.33  5148.2 2185.20  5175.0 2186.56  5176.9 2186.56
#Mann=7,-1,0
  4705.2    0.07       0  4705.7   0.035       0  4834.9    0.07       0
  4947.8    0.16       0  5001.1    0.07       0  5005.1    0.16       0
  5175.0    0.07       0
Bank Sta=5001.1,5005.1
Exp/Cntr=0.3,0.1

Type RM Length L Ch R = 1,1437,38,38,38
BEGIN DESCRIPTION:
elmc464
END DESCRIPTION:
XS GIS Cut Line= 3
      1515139.33      6770467.59      1515247.41      6770277.46
      1515363.30      6770175.89
#Sta/Elev= 30
  4781.2 2172.92  4784.5 2173.48  4800.4 2165.47  4806.1 2165.70  4822.0 2160.28
  4827.8 2161.12  4837.9 2157.95  4843.6 2158.66  4849.7 2154.82  4859.5 2153.07
  4865.2 2153.34  4882.8 2145.76  4925.6 2145.78  4953.3 2145.44  4961.8 2143.32
  4976.3 2141.89  4983.5 2142.61  5009.7 2141.46  5009.9 2140.96  5013.7 2141.46
  5033.5 2141.67  5047.7 2145.06  5054.4 2148.40  5076.2 2153.08  5103.7 2162.60
  5117.9 2165.27  5132.2 2169.89  5139.8 2174.19  5151.8 2178.95  5154.0 2178.95
#Mann=5,-1,0
  4781.2   0.035       0  4882.8    0.07       0  4925.6    0.16       0
  5009.7    0.07       0  5013.7    0.16       0
Bank Sta=5009.7,5013.7
Exp/Cntr=0.3,0.1

Type RM Length L Ch R = 1,1399,41,41,41
BEGIN DESCRIPTION:
elmc465
END DESCRIPTION:
XS GIS Cut Line= 3
      1515161.48      6770474.07      1515281.26      6770289.18
      1515389.04      6770182.70
#Sta/Elev= 30
  4778.1 2178.13  4792.5 2168.52  4798.5 2166.34  4807.7 2165.22  4821.1 2159.13
  4828.8 2158.98  4834.8 2155.12  4843.9 2154.44  4849.9 2151.44  4865.1 2150.27
  4871.0 2146.80  4890.0 2144.15  4896.9 2144.67  4922.4 2145.05  4995.2 2140.50
  4995.5 2140.00  4999.2 2140.50  5016.1 2140.86  5037.2 2143.92  5058.5 2152.87
  5086.8 2160.28  5093.8 2163.04  5100.9 2164.21  5107.9 2168.07  5115.1 2169.04
  5122.1 2172.69  5129.2 2173.75  5136.2 2176.97  5143.3 2177.30  5149.9 2180.23
#Mann=5,-1,0
  4778.1   0.035       0  4890.0    0.07       0  4896.9    0.16       0
  4995.2    0.07       0  4999.2    0.16       0
Bank Sta=4995.2,4999.2
Exp/Cntr=0.3,0.1

Type RM Length L Ch R = 1,1358,43,43,43
BEGIN DESCRIPTION:
elmc463
END DESCRIPTION:
XS GIS Cut Line= 3
      1515166.65      6770472.80      1515320.33      6770303.50
      1515395.77      6770192.94
#Sta/Elev= 30
  4772.5 2172.89  4781.6 2171.67  4789.1 2166.34  4795.8 2165.39  4803.2 2162.35
  4810.0 2162.22  4817.4 2157.07  4824.2 2157.61  4831.6 2153.70  4838.4 2153.48
  4845.8 2150.38  4852.6 2150.63  4860.0 2147.92  4864.1 2147.69  4866.8 2147.54
  4873.5 2144.76  4881.0 2143.81  4896.6 2144.20  4992.5 2140.07  4992.7 2139.57
  4996.5 2140.07  5016.1 2141.88  5037.1 2147.92  5052.0 2153.96  5073.0 2156.55
  5087.9 2162.20  5108.9 2166.44  5123.8 2173.75  5129.8 2173.95  5135.0 2176.91
#Mann=5,-1,0
  4772.5   0.035       0  4864.1    0.07       0  4896.6    0.16       0
  4992.5    0.07       0  4996.5    0.16       0
Bank Sta=4992.5,4996.5
Exp/Cntr=0.3,0.1

Type RM Length L Ch R = 1,1315,61,61,61
BEGIN DESCRIPTION:
elmc462
END DESCRIPTION:
XS GIS Cut Line= 3
      1515217.49      6770462.33      1515348.97      6770336.05
      1515409.67      6770252.59
#Sta/Elev= 30
  4815.1 2167.19  4823.6 2163.46  4828.0 2160.99  4830.5 2159.58  4837.7 2156.63
  4844.7 2154.59  4851.9 2151.48  4858.8 2149.64  4866.0 2147.10  4880.2 2144.29
  4887.1 2143.05  4901.3 2143.15  4930.7 2141.89  4943.7 2141.31  4950.6 2141.43
  4957.9 2140.57  4978.9 2140.34  4986.2 2139.51  5005.4 2139.26  5005.6 2138.76
  5009.1 2138.76  5009.4 2139.26  5029.5 2142.78  5056.8 2150.39  5065.1 2151.74
  5071.3 2152.26  5079.8 2153.80  5085.9 2153.74  5093.9 2155.50  5100.6 2158.29
#Mann=5,-1,0
  4815.1   0.035       0  4828.0    0.07       0  4930.7    0.16       0
  5005.4    0.07       0  5009.4    0.16       0
Bank Sta=5005.4,5009.4
Exp/Cntr=0.3,0.1

Type RM Length L Ch R = 1,1254,65,65,65
BEGIN DESCRIPTION:
elmc461
END DESCRIPTION:
XS GIS Cut Line= 3
      1515263.07      6770507.89      1515391.94      6770380.32
      1515453.12      6770263.17
#Sta/Elev= 30
  4813.6 2163.04  4817.1 2163.04  4822.0 2158.62  4829.1 2156.92  4836.1 2153.19
  4843.2 2150.97  4853.3 2146.78  4857.3 2145.21  4871.5 2142.60  4878.5 2142.12
  4902.2 2142.11  4921.0 2141.12  4928.1 2140.14  4942.2 2139.65  4949.2 2139.97
  4956.3 2139.30  4963.4 2139.55  4982.6 2138.49  4982.9 2137.99  4986.4 2137.99
  4986.6 2138.49  4999.1 2138.68  5020.1 2141.46  5057.6 2144.33  5065.2 2145.80
  5079.7 2147.05  5101.7 2151.34  5110.4 2153.86  5118.2 2156.99  5127.1 2157.93
#Mann=5,-1,0
  4813.6   0.035       0  4853.3    0.07       0  4902.2    0.16       0
  4982.6    0.07       0  4986.6    0.16       0
Bank Sta=4982.6,4986.6
Exp/Cntr=0.3,0.1

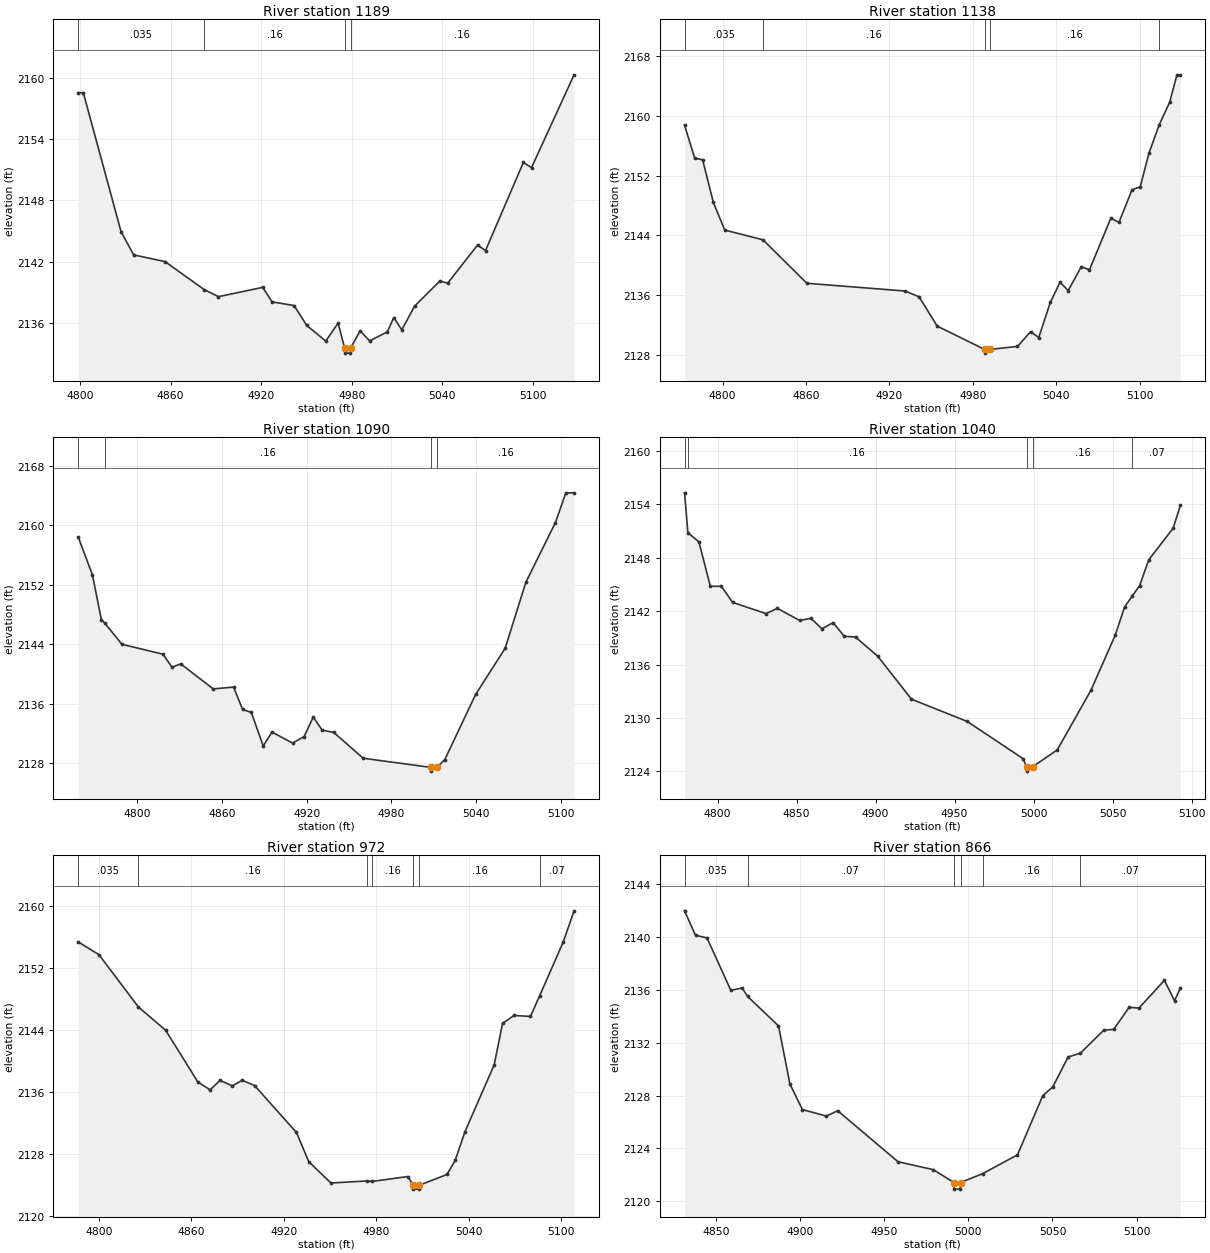
Type RM Length L Ch R = 1,1189,51,51,51
BEGIN DESCRIPTION:
elmc460
END DESCRIPTION:
XS GIS Cut Line= 3
      1515335.93      6770549.62      1515457.05      6770386.83
      1515500.65      6770268.84
#Sta/Elev= 30
  4798.7 2158.54  4802.1 2158.54  4827.1 2144.93  4835.5 2142.66  4856.3 2142.00
  4882.3 2139.25  4891.7 2138.57  4921.0 2139.48  4927.2 2138.06  4941.8 2137.70
  4950.2 2135.75  4962.8 2134.22  4971.0 2135.99  4975.3 2133.54  4975.5 2133.04
  4979.0 2133.04  4979.3 2133.54  4985.6 2135.22  4991.9 2134.24  5003.6 2135.12
  5007.9 2136.52  5013.2 2135.32  5021.7 2137.64  5038.3 2140.08  5043.7 2139.90
  5063.4 2143.62  5068.7 2143.08  5093.8 2151.71  5099.2 2151.20  5127.4 2160.29
#Mann=4,-1,0
  4798.7   0.035       0  4882.3    0.16       0  4975.3    0.07       0
  4979.3    0.16       0
Bank Sta=4975.3,4979.3
Exp/Cntr=0.3,0.1

Type RM Length L Ch R = 1,1138,48,48,48
BEGIN DESCRIPTION:
elmc458
END DESCRIPTION:
XS GIS Cut Line= 3
      1515394.55      6770586.04      1515509.13      6770384.23
      1515575.54      6770278.76
#Sta/Elev= 30
  4772.6 2158.76  4779.9 2154.34  4785.6 2154.12  4793.3 2148.41  4801.5 2144.70
  4829.0 2143.39  4860.6 2137.56  4931.3 2136.52  4941.4 2135.73  4954.3 2131.82
  4988.4 2128.69  4988.6 2128.19  4992.4 2128.69  5012.1 2129.09  5021.5 2131.06
  5027.4 2130.28  5035.7 2134.99  5042.7 2137.70  5048.6 2136.58  5058.0 2139.79
  5063.9 2139.37  5079.2 2146.28  5085.1 2145.73  5094.5 2150.10  5100.4 2150.50
  5106.6 2154.97  5114.1 2158.84  5121.6 2161.86  5126.8 2165.52  5129.3 2165.52
#Mann=5,-1,0
  4772.6   0.035       0  4829.0    0.16       0  4988.4    0.07       0
  4992.4    0.16       0  5114.1    0.07       0
Bank Sta=4988.4,4992.4
Exp/Cntr=0.3,0.1

Type RM Length L Ch R = 1,1090,50,50,50
BEGIN DESCRIPTION:
elmc457
END DESCRIPTION:
XS GIS Cut Line= 3
      1515410.16      6770586.06      1515557.31      6770389.44
      1515618.51      6770303.49
#Sta/Elev= 30
  4758.2 2158.40  4768.3 2153.30  4774.6 2147.31  4777.0 2146.83  4789.2 2143.99
  4818.2 2142.66  4824.6 2140.92  4830.8 2141.36  4853.8 2138.00  4868.2 2138.24
  4874.6 2135.24  4880.8 2134.83  4889.2 2130.33  4895.4 2132.19  4910.0 2130.72
  4918.2 2131.60  4924.6 2134.22  4930.9 2132.47  4939.2 2132.14  4960.0 2128.68
  5008.1 2127.45  5008.3 2126.95  5012.1 2127.45  5017.8 2128.51  5039.6 2137.25
  5060.5 2143.45  5075.2 2152.33  5096.1 2160.34  5103.5 2164.34  5109.3 2164.34
#Mann=4,-1,0
  4758.2   0.035       0  4777.0    0.16       0  5008.1    0.07       0
  5012.1    0.16       0
Bank Sta=5008.1,5012.1
Exp/Cntr=0.3,0.1

Type RM Length L Ch R = 1,1040,68,68,68
BEGIN DESCRIPTION:
elmc459
END DESCRIPTION:
XS GIS Cut Line= 3
      1515437.48      6770583.48      1515591.16      6770427.20
      1515640.96      6770346.75
#Sta/Elev= 30
  4779.1 2155.26  4781.2 2150.79  4788.2 2149.75  4795.4 2144.78  4802.4 2144.77
  4809.5 2142.97  4830.7 2141.71  4837.8 2142.30  4852.0 2140.94  4859.0 2141.18
  4866.1 2140.01  4873.1 2140.70  4880.2 2139.17  4887.3 2139.08  4901.4 2136.92
  4922.7 2132.11  4958.0 2129.61  4993.4 2125.43  4995.5 2124.54  4995.7 2124.04
  4999.5 2124.54  5015.0 2126.43  5036.3 2133.12  5051.7 2139.31  5057.6 2142.47
  5062.5 2143.70  5067.1 2144.86  5072.9 2147.75  5088.3 2151.29  5092.9 2153.88
#Mann=5,-1,0
  4779.1   0.035       0  4781.2    0.16       0  4995.5    0.07       0
  4999.5    0.16       0  5062.5    0.07       0
Bank Sta=4995.5,4999.5
Exp/Cntr=0.3,0.1

Type RM Length L Ch R = 1,972,106,106,106
BEGIN DESCRIPTION:
elmc456
END DESCRIPTION:
XS GIS Cut Line= 3
      1515475.30      6770608.17      1515638.04      6770477.98
      1515676.55      6770371.43
#Sta/Elev= 30
  4786.7 2155.43  4800.2 2153.76  4825.7 2147.02  4843.5 2143.98  4864.3 2137.31
  4872.3 2136.29  4878.7 2137.51  4886.7 2136.81  4893.1 2137.52  4901.1 2136.85
  4928.3 2130.78  4936.3 2126.99  4950.7 2124.24  4974.1 2124.51  4977.3 2124.44
  5000.6 2125.08  5004.0 2123.95  5004.2 2123.45  5007.7 2123.45  5008.0 2123.95
  5026.0 2125.35  5031.3 2127.18  5037.6 2130.87  5056.6 2139.53  5062.0 2144.87
  5069.5 2145.91  5080.1 2145.78  5086.1 2148.47  5101.4 2155.42  5108.4 2159.44
#Mann=7,-1,0
  4786.7   0.035       0  4825.7    0.16       0  4974.1    0.07       0
  4977.3    0.16       0  5004.0    0.07       0  5008.0    0.16       0
  5086.1    0.07       0
Bank Sta=5004,5008
Exp/Cntr=0.3,0.1

Type RM Length L Ch R = 1,866,67,67,67
BEGIN DESCRIPTION:
elmc455
END DESCRIPTION:
XS GIS Cut Line= 3
      1515589.83      6770661.60      1515713.56      6770549.59
      1515783.79      6770442.94
#Sta/Elev= 30
  4831.4 2141.95  4837.9 2140.10  4844.7 2139.91  4858.9 2135.94  4865.6 2136.13
  4868.8 2135.49  4887.2 2133.26  4894.0 2128.87  4901.4 2126.94  4915.6 2126.45
  4922.4 2126.85  4958.2 2123.00  4979.2 2122.40  4991.4 2121.43  4991.6 2120.93
  4995.1 2120.93  4995.4 2121.43  5008.5 2122.10  5029.2 2123.52  5044.2 2127.98
  5050.2 2128.66  5059.3 2130.91  5066.6 2131.20  5080.4 2132.93  5086.4 2133.00
  5095.5 2134.66  5101.4 2134.61  5116.5 2136.70  5122.5 2135.16  5126.0 2136.13
#Mann=6,-1,0
  4831.4   0.035       0  4868.8    0.07       0  4991.4    0.07       0
  4995.4    0.07       0  5008.5    0.16       0  5066.6    0.07       0
Bank Sta=4991.4,4995.4
Exp/Cntr=0.3,0.1

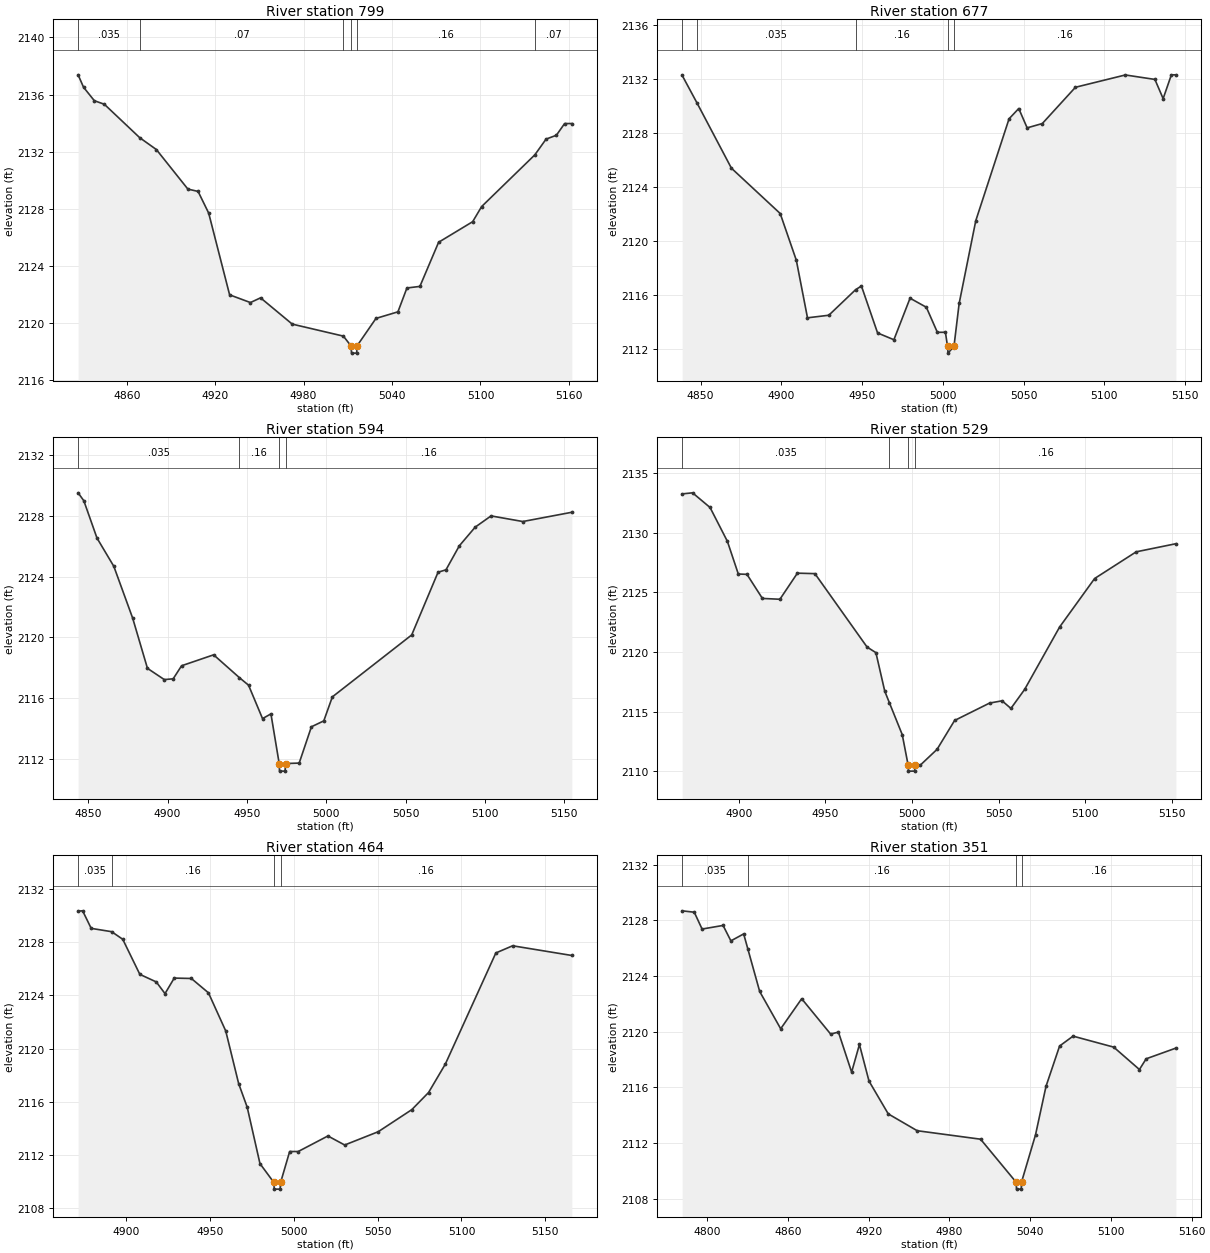
Type RM Length L Ch R = 1,799,122,122,122
BEGIN DESCRIPTION:
elmc454
END DESCRIPTION:
XS GIS Cut Line= 3
      1515636.72      6770714.97      1515768.24      6770589.96
      1515855.51      6770463.62
#Sta/Elev= 30
  4827.0 2137.38  4830.7 2136.51  4838.0 2135.57  4844.8 2135.32  4868.8 2132.98
  4880.1 2132.15  4901.5 2129.38  4908.4 2129.22  4915.6 2127.70  4929.8 2121.98
  4943.9 2121.44  4950.8 2121.77  4972.3 2119.93  5007.0 2119.09  5012.2 2118.40
  5012.5 2117.90  5016.0 2117.90  5016.2 2118.40  5029.1 2120.33  5044.0 2120.79
  5050.1 2122.46  5058.9 2122.57  5071.6 2125.66  5094.7 2127.10  5100.8 2128.16
  5136.9 2131.78  5144.5 2132.88  5151.5 2133.15  5157.1 2133.97  5162.0 2133.97
#Mann=6,-1,0
  4827.0   0.035       0  4868.8    0.07       0  5007.0    0.16       0
  5012.2    0.07       0  5016.2    0.16       0  5136.9    0.07       0
Bank Sta=5012.2,5016.2
Exp/Cntr=0.3,0.1

Type RM Length L Ch R = 1,677,83,83,83
BEGIN DESCRIPTION:
elmc453
END DESCRIPTION:
XS GIS Cut Line= 3
      1515851.57      6770798.33      1515868.50      6770639.44
      1515902.36      6770497.51
#Sta/Elev= 30
  4838.6 2132.26  4847.8 2130.22  4869.1 2125.40  4899.3 2122.05  4909.3 2118.59
  4916.2 2114.34  4929.4 2114.53  4946.0 2116.42  4949.6 2116.69  4959.6 2113.22
  4969.7 2112.72  4979.7 2115.79  4989.8 2115.12  4996.6 2113.27  5001.6 2113.27
  5002.9 2112.23  5003.2 2111.73  5006.9 2112.23  5010.1 2115.40  5020.4 2121.52
  5041.0 2129.05  5047.0 2129.81  5052.2 2128.38  5061.6 2128.70  5082.1 2131.38
  5113.0 2132.29  5131.3 2131.96  5136.4 2130.54  5141.5 2132.30  5144.3 2132.30
#Mann=5,-1,0
  4838.6    0.07       0  4847.8   0.035       0  4946.0    0.16       0
  5002.9    0.07       0  5006.9    0.16       0
Bank Sta=5002.9,5006.9
Exp/Cntr=0.3,0.1

Type RM Length L Ch R = 1,594,65,65,65
BEGIN DESCRIPTION:
elmc452
END DESCRIPTION:
XS GIS Cut Line= 3
      1515899.76      6770789.16      1515951.84      6770643.34
      1515947.93      6770487.13
#Sta/Elev= 30
  4843.6 2129.52  4847.2 2129.00  4855.5 2126.54  4866.1 2124.68  4878.0 2121.26
  4887.3 2117.96  4897.9 2117.22  4903.5 2117.27  4908.8 2118.13  4929.0 2118.85
  4945.2 2117.35  4951.0 2116.85  4959.8 2114.65  4965.1 2114.96  4970.3 2111.69
  4970.5 2111.19  4974.0 2111.19  4974.3 2111.69  4982.9 2111.72  4990.6 2114.11
  4998.4 2114.50  5003.8 2116.08  5053.8 2120.16  5070.4 2124.29  5075.4 2124.45
  5083.8 2126.03  5093.8 2127.26  5103.8 2128.00  5123.8 2127.63  5154.7 2128.24
#Mann=4,-1,0
  4843.6   0.035       0  4945.2    0.16       0  4970.3    0.07       0
  4974.3    0.16       0
Bank Sta=4970.3,4974.3
Exp/Cntr=0.3,0.1

Type RM Length L Ch R = 1,529,65,65,65
BEGIN DESCRIPTION:
elmc389
END DESCRIPTION:
XS GIS Cut Line= 3
      1515985.69      6770813.92      1516002.69      6770682.31
      1516023.25      6770531.51
#Sta/Elev= 30
  4867.3 2133.26  4873.3 2133.35  4883.4 2132.12  4893.4 2129.28  4899.7 2126.54
  4904.7 2126.51  4913.6 2124.49  4923.7 2124.42  4933.8 2126.61  4943.9 2126.57
  4974.0 2120.41  4979.1 2119.94  4984.2 2116.71  4986.9 2115.73  4994.3 2113.06
  4997.7 2110.50  4997.9 2110.00  5001.4 2110.00  5001.7 2110.50  5004.7 2110.50
  5014.4 2111.83  5024.5 2114.25  5044.7 2115.71  5051.9 2115.90  5057.0 2115.26
  5064.9 2116.85  5085.1 2122.09  5105.3 2126.16  5129.3 2128.40  5152.2 2129.08
#Mann=4,-1,0
  4867.3   0.035       0  4986.9    0.16       0  4997.7    0.07       0
  5001.7    0.16       0
Bank Sta=4997.7,5001.7
Exp/Cntr=0.3,0.1

Type RM Length L Ch R = 1,464,113,113,113
BEGIN DESCRIPTION:
elmc451
END DESCRIPTION:
XS GIS Cut Line= 3
      1516039.07      6770813.95      1516066.42      6770688.39
      1516061.23      6770522.67
#Sta/Elev= 30
  4871.5 2130.35  4874.2 2130.37  4879.3 2129.05  4891.5 2128.80  4898.1 2128.23
  4908.3 2125.59  4918.1 2125.02  4923.3 2124.14  4928.8 2125.31  4939.0 2125.28
  4949.2 2124.20  4959.5 2121.33  4967.2 2117.37  4972.3 2115.59  4979.9 2111.35
  4988.2 2109.93  4988.4 2109.43  4991.9 2109.43  4992.2 2109.93  4997.6 2112.26
  5002.7 2112.26  5020.4 2113.43  5030.4 2112.75  5050.4 2113.75  5070.4 2115.41
  5080.4 2116.70  5090.4 2118.84  5120.5 2127.20  5130.5 2127.74  5165.8 2127.01
#Mann=4,-1,0
  4871.5   0.035       0  4891.5    0.16       0  4988.2    0.07       0
  4992.2    0.16       0
Bank Sta=4988.2,4992.2
Exp/Cntr=0.3,0.1

Type RM Length L Ch R = 1,351,110,110,110
BEGIN DESCRIPTION:
elmc450
END DESCRIPTION:
XS GIS Cut Line= 3
      1516053.42      6770837.32      1516164.93      6770649.42
      1516147.24      6770502.18
#Sta/Elev= 30
  4781.5 2128.69  4790.5 2128.59  4796.3 2127.38  4811.9 2127.64  4817.7 2126.53
  4827.2 2127.03  4830.3 2125.95  4839.1 2122.89  4854.7 2120.21  4870.3 2122.37
  4891.8 2119.83  4897.6 2119.97  4907.4 2117.09  4913.2 2119.08  4920.3 2116.45
  4934.6 2114.09  4956.1 2112.88  5003.2 2112.27  5029.6 2109.18  5029.9 2108.68
  5033.4 2108.68  5033.6 2109.18  5044.0 2112.58  5051.8 2116.07  5061.9 2118.97
  5071.9 2119.68  5102.1 2118.89  5121.2 2117.28  5126.2 2118.05  5148.3 2118.82
#Mann=4,-1,0
  4781.5   0.035       0  4830.3    0.16       0  5029.6    0.07       0
  5033.6    0.16       0
Bank Sta=5029.6,5033.6
Exp/Cntr=0.3,0.1