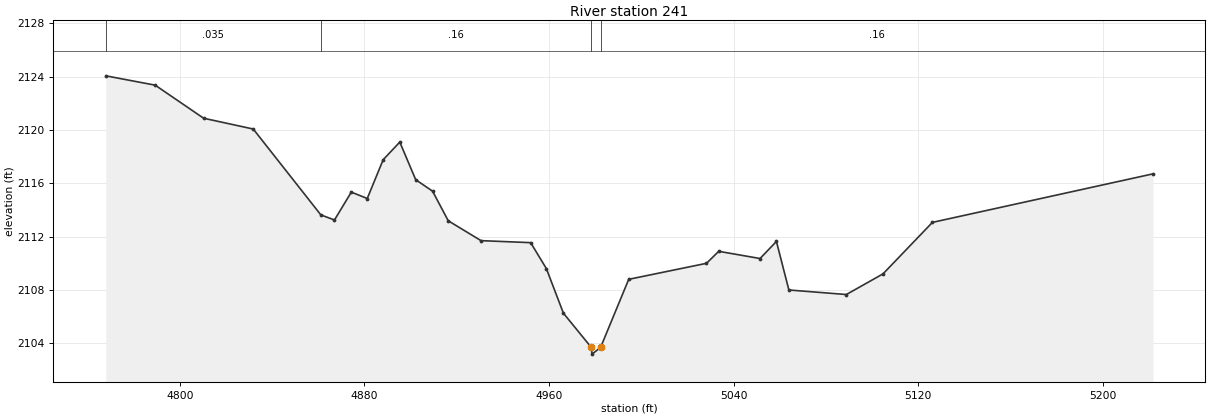
HEC-RAS study Elm 55.prj: Elm 55 Base Level Engineering

--- Elm 55.g01 (geometry) --- (continued)

Type RM Length L Ch R = 1,241,0,0,0
BEGIN DESCRIPTION:
elmc449
END DESCRIPTION:
XS GIS Cut Line= 3
      1516102.91      6770865.97      1516261.09      6770696.12
      1516183.61      6770488.40
#Sta/Elev= 30
  4767.9 2124.07  4789.3 2123.37  4810.3 2120.89  4831.8 2120.08  4861.1 2113.64
  4867.0 2113.26  4874.3 2115.35  4881.2 2114.87  4888.1 2117.78  4895.3 2119.10
  4902.2 2116.28  4909.5 2115.42  4916.3 2113.20  4930.5 2111.71  4952.0 2111.56
  4958.8 2109.62  4966.2 2106.27  4978.3 2103.70  4978.6 2103.20  4982.3 2103.70
  4994.5 2108.81  5028.2 2110.01  5033.5 2110.91  5051.4 2110.37  5058.5 2111.65
  5063.9 2108.01  5088.8 2107.67  5104.7 2109.22  5126.1 2113.08  5221.7 2116.72
#Mann=4,-1,0
  4767.9   0.035       0  4861.1    0.16       0  4978.3    0.07       0
  4982.3    0.16       0
Bank Sta=4978.3,4982.3
Exp/Cntr=0.3,0.1

Chan Stop Cuts=-1