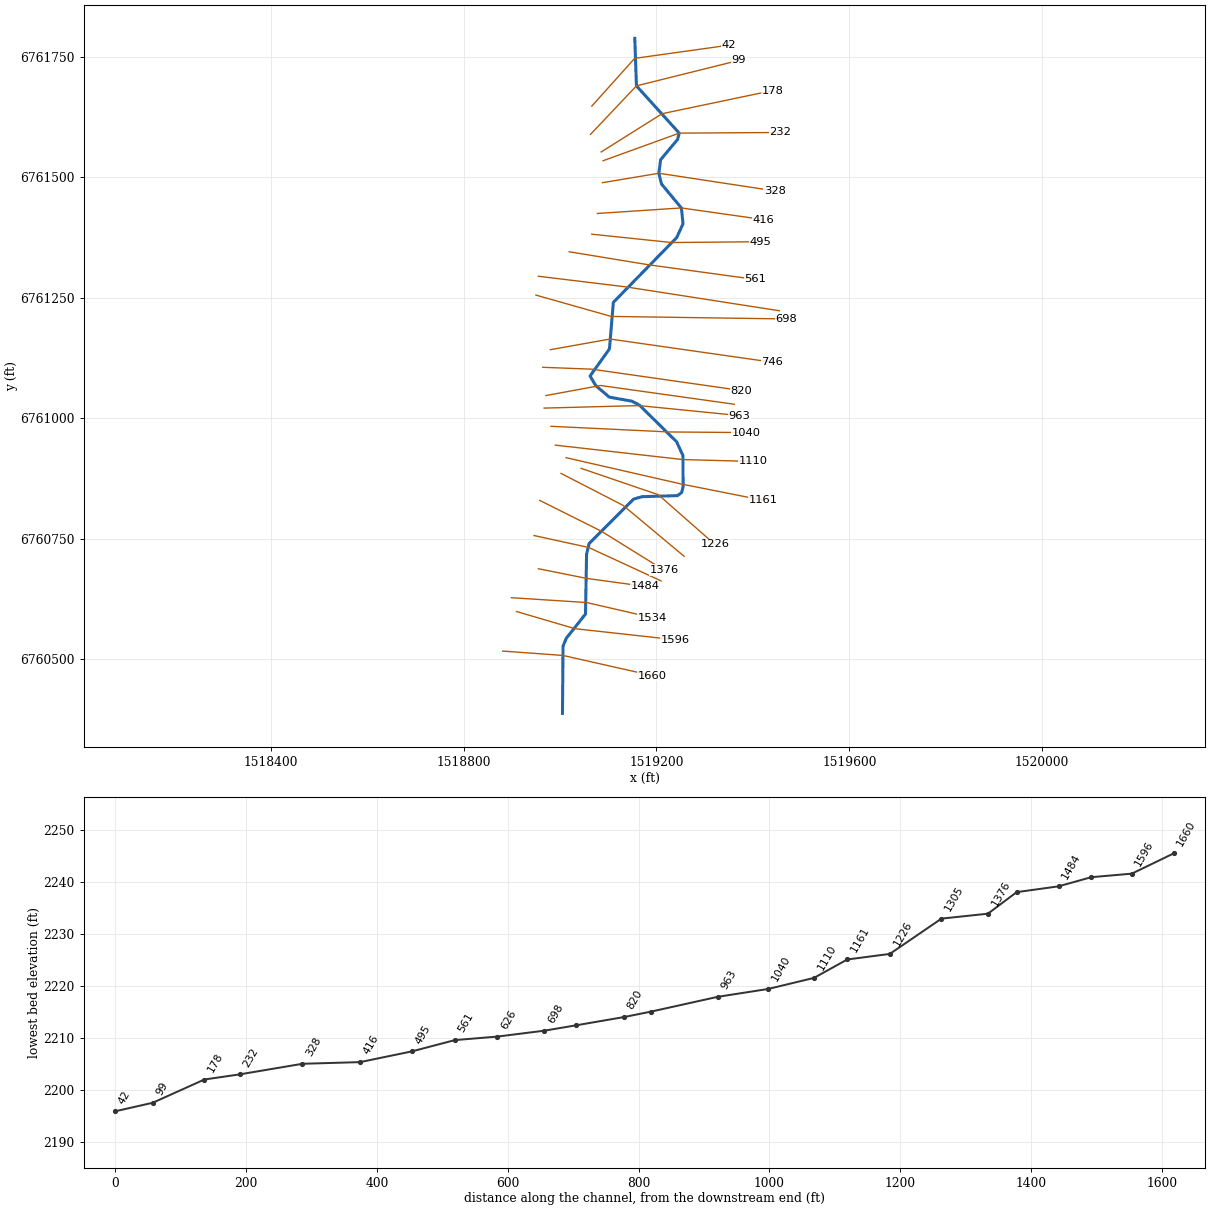
--- Elm 56.prj (project) ---

Proj Title=Elm 56 Base Level Engineering
Current Plan=p01
Default Exp/Contr=0.3,0.1
English Units
Geom File=g01
Flow File=f01
Plan File=p01
BEGIN DESCRIPTION:
Elm 56
END DESCRIPTION:

--- Elm 56.p01 (plan) ---

Plan Title=Multiple Run
Short Identifier=Multiple
Geom File=g01
Flow File=f01
Subcritical Flow
K Sum by GR= 0
Std Step Tol= 0.01
Critical Tol= 0.01
Num of Std Step Trials= 20
Max Error Tol= 0.3
Flow Tol Ratio= 0.001
Split Flow NTrial= 30
Split Flow Tol= 0.02
Split Flow Ratio= 0.02
Log Output Level= 0
Friction Slope Method= 1
Unsteady Friction Slope Method= 2
Unsteady Bridges Friction Slope Method= 1
Parabolic Critical Depth
Global Vel Dist=  1 , 1 , 1
Global Log Level= 0
CheckData=True
Encroach Param= -1, 0, 0, 0
BEGIN DESCRIPTION:
Multiple Run
END DESCRIPTION:

--- Elm 56.f01 (steady flow) ---

Flow Title=Multiple
Number of Profiles=7
Profile Names=10-year,25-year,50-year,1pct_min,100-year,1pct_plu,500-year
River Rch & RM= Elm 56,Reach-1,1660
     196     272     336     259     415     571     638
River Rch & RM= Elm 56,Reach-1,42
     426     617     782     616     987    1360    1590
Boundary for River Rch & Prof#=Elm 56,Reach-1,1
Up Type=0
Dn Type=3
Dn Slope=0.005
Boundary for River Rch & Prof#=Elm 56,Reach-1,2
Up Type=0
Dn Type=3
Dn Slope=0.005
Boundary for River Rch & Prof#=Elm 56,Reach-1,3
Up Type=0
Dn Type=3
Dn Slope=0.005
Boundary for River Rch & Prof#=Elm 56,Reach-1,4
Up Type=0
Dn Type=3
Dn Slope=0.005
Boundary for River Rch & Prof#=Elm 56,Reach-1,5
Up Type=0
Dn Type=3
Dn Slope=0.005
Boundary for River Rch & Prof#=Elm 56,Reach-1,6
Up Type=0
Dn Type=3
Dn Slope=0.005
Boundary for River Rch & Prof#=Elm 56,Reach-1,7
Up Type=0
Dn Type=3
Dn Slope=0.005

--- Elm 56.g01 (geometry) ---

Geom Title=Existing Conditions

River Reach=Elm 56,Reach-1
Reach XY= 30
      1519005.00      6760388.00      1519006.17      6760527.52
      1519013.13      6760544.06      1519052.73      6760593.94
      1519054.98      6760718.01      1519060.46      6760740.46
      1519152.62      6760832.46      1519170.36      6760837.42
      1519243.52      6760839.62      1519252.16      6760846.01
      1519255.22      6760858.05      1519254.83      6760922.64
      1519241.69      6760951.30      1519164.67      6761027.23
      1519148.88      6761035.47      1519102.15      6761043.85
      1519074.13      6761067.58      1519062.23      6761087.69
      1519102.43      6761143.88      1519110.52      6761240.43
      1519241.88      6761374.79      1519255.04      6761403.34
      1519251.63      6761436.26      1519210.44      6761485.81
      1519204.81      6761508.20      1519208.62      6761536.37
      1519243.61      6761578.13      1519247.17      6761591.40
      1519158.41      6761689.40      1519155.00      6761788.00

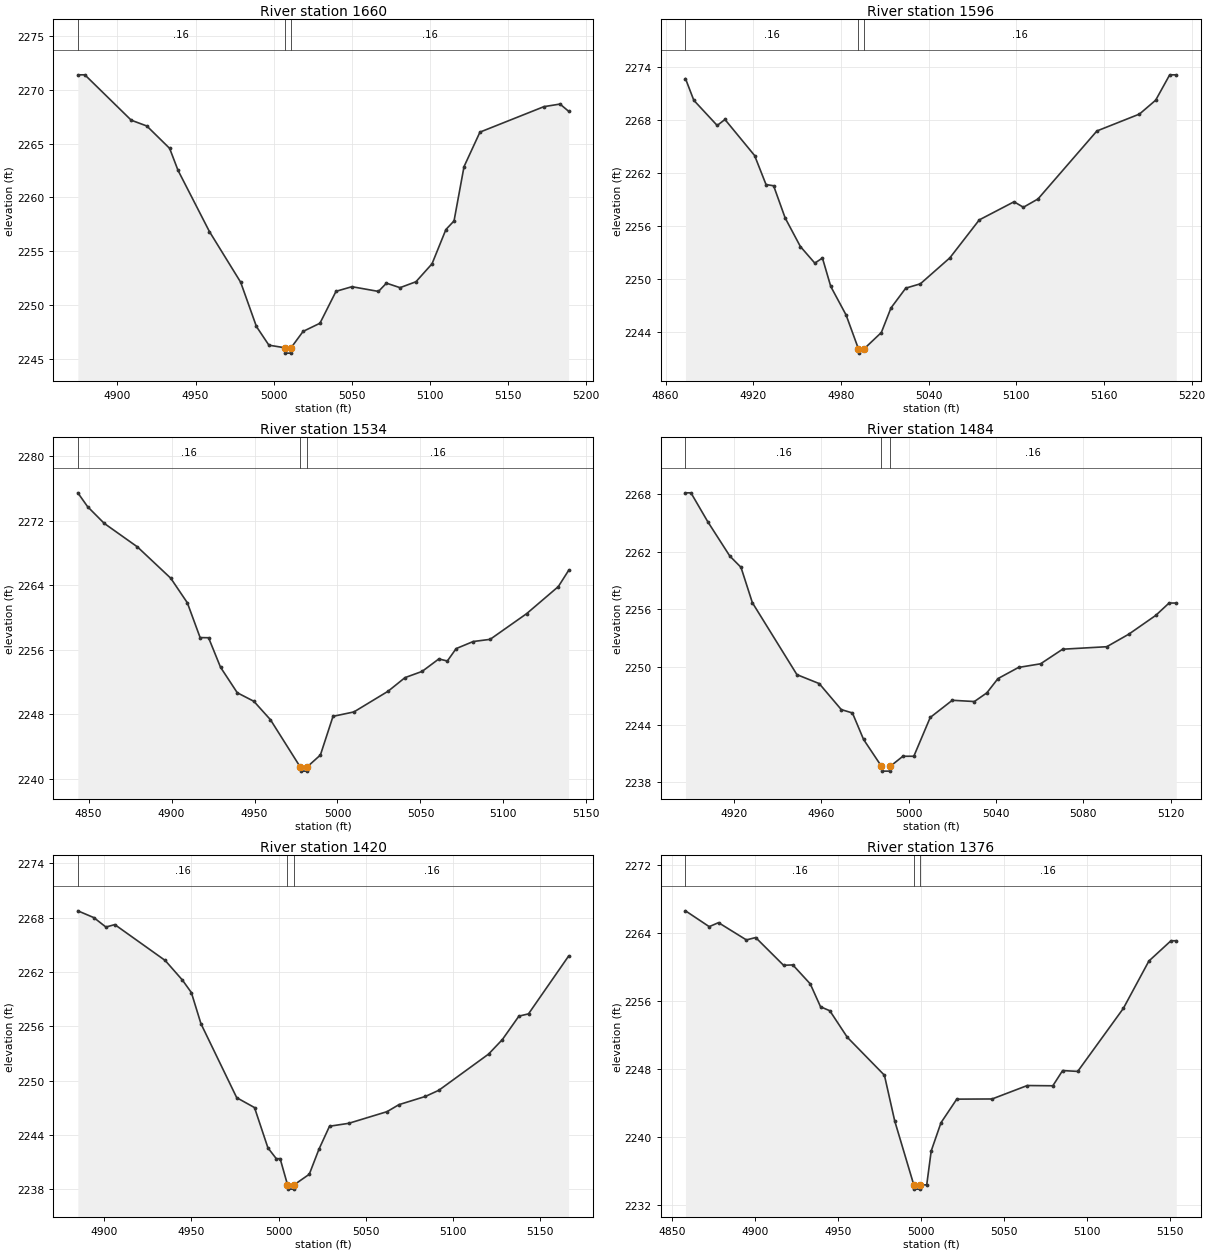
Type RM Length L Ch R = 1,1660,64,64,64
BEGIN DESCRIPTION:
Elm 56 4780
END DESCRIPTION:
XS GIS Cut Line= 3
      1518880.93      6760517.23      1519006.01      6760508.15
      1519190.37      6760466.55
#Sta/Elev= 30
  4874.6 2271.39  4879.1 2271.39  4908.8 2267.17  4918.8 2266.63  4933.4 2264.55
  4938.8 2262.50  4958.9 2256.81  4978.9 2252.10  4989.0 2247.98  4997.0 2246.24
  5007.2 2246.00  5007.5 2245.50  5011.0 2245.50  5011.2 2246.00  5018.9 2247.52
  5029.7 2248.28  5040.0 2251.25  5050.2 2251.68  5067.2 2251.24  5072.3 2252.01
  5081.0 2251.59  5091.2 2252.14  5101.5 2253.81  5110.4 2257.00  5115.6 2257.80
  5122.0 2262.85  5132.2 2266.06  5173.2 2268.43  5183.5 2268.67  5189.0 2268.00
#Mann=3,-1,0
  4874.6    0.16       0  5007.2    0.07       0  5011.2    0.16       0
Bank Sta=5007.2,5011.2
Exp/Cntr=0.3,0.1

Type RM Length L Ch R = 1,1596,62,62,62
BEGIN DESCRIPTION:
Elm 56 4781
END DESCRIPTION:
XS GIS Cut Line= 3
      1518909.57      6760599.25      1519030.86      6760563.66
      1519238.99      6760540.67
#Sta/Elev= 30
  4873.6 2272.65  4879.3 2270.20  4895.3 2267.35  4900.6 2268.03  4920.9 2263.95
  4928.7 2260.67  4933.9 2260.53  4941.8 2256.89  4952.2 2253.66  4962.1 2251.78
  4967.3 2252.36  4973.0 2249.14  4983.5 2245.91  4991.9 2242.10  4992.1 2241.60
  4995.9 2242.10  5007.6 2243.93  5014.2 2246.71  5024.3 2248.95  5034.3 2249.44
  5054.5 2252.38  5074.6 2256.67  5098.4 2258.72  5104.8 2258.10  5114.8 2259.04
  5155.1 2266.73  5184.2 2268.64  5195.3 2270.21  5204.9 2273.08  5209.4 2273.08
#Mann=3,-1,0
  4873.6    0.16       0  4991.9    0.07       0  4995.9    0.16       0
Bank Sta=4991.9,4995.9
Exp/Cntr=0.3,0.1

Type RM Length L Ch R = 1,1534,50,50,50
BEGIN DESCRIPTION:
Elm 56 4779
END DESCRIPTION:
XS GIS Cut Line= 3
      1518899.15      6760627.91      1519055.32      6760617.87
      1519191.04      6760586.49
#Sta/Elev= 30
  4843.5 2275.47  4849.4 2273.75  4859.4 2271.68  4879.4 2268.76  4899.5 2264.87
  4909.5 2261.82  4917.2 2257.50  4922.3 2257.48  4929.5 2253.82  4939.6 2250.65
  4949.6 2249.59  4959.6 2247.30  4977.6 2241.42  4977.9 2240.92  4981.4 2240.92
  4981.6 2241.42  4989.7 2242.92  4997.3 2247.72  5009.9 2248.27  5030.5 2250.84
  5040.7 2252.53  5051.0 2253.30  5061.1 2254.85  5066.2 2254.59  5071.5 2256.13
  5081.8 2257.01  5092.0 2257.28  5114.0 2260.47  5133.1 2263.83  5139.3 2265.84
#Mann=3,-1,0
  4843.5    0.16       0  4977.6    0.07       0  4981.6    0.16       0
Bank Sta=4977.6,4981.6
Exp/Cntr=0.3,0.1

Type RM Length L Ch R = 1,1484,64,64,64
BEGIN DESCRIPTION:
Elm 56 1484.38
END DESCRIPTION:
XS GIS Cut Line= 3
      1518955.04      6760687.99      1519055.15      6760667.94
      1519176.52      6760651.34
#Sta/Elev= 30
  4897.9 2268.15  4900.4 2268.15  4908.1 2265.14  4918.2 2261.56  4923.3 2260.39
  4928.5 2256.71  4948.9 2249.21  4959.1 2248.28  4969.2 2245.57  4974.3 2245.22
  4979.4 2242.46  4987.6 2239.66  4987.9 2239.16  4991.4 2239.16  4991.6 2239.66
  4997.4 2240.71  5002.4 2240.71  5009.9 2244.75  5020.0 2246.54  5030.1 2246.41
  5035.8 2247.31  5040.9 2248.80  5050.3 2249.96  5060.4 2250.34  5070.5 2251.86
  5090.7 2252.12  5100.8 2253.43  5113.1 2255.38  5119.2 2256.67  5122.5 2256.67
#Mann=3,-1,0
  4897.9    0.16       0  4987.6    0.07       0  4991.6    0.16       0
Bank Sta=4987.6,4991.6
Exp/Cntr=0.3,0.1

Type RM Length L Ch R = 1,1420,44,44,44
BEGIN DESCRIPTION:
Elm 56 1419.64
END DESCRIPTION:
XS GIS Cut Line= 3
      1518946.01      6760756.81      1519059.29      6760732.07
      1519209.51      6760662.74
#Sta/Elev= 30
  4884.9 2268.75  4894.1 2268.00  4901.0 2266.96  4906.1 2267.23  4935.0 2263.27
  4944.9 2261.10  4950.0 2259.73  4955.5 2256.29  4976.0 2248.13  4986.2 2247.04
  4993.9 2242.59  4998.7 2241.40  5000.9 2241.40  5005.1 2238.54  5005.4 2238.04
  5008.9 2238.04  5009.1 2238.54  5017.6 2239.68  5023.1 2242.42  5029.2 2244.98
  5040.2 2245.30  5062.2 2246.59  5069.0 2247.36  5084.2 2248.27  5091.9 2248.95
  5120.4 2252.94  5128.3 2254.54  5137.8 2257.13  5143.3 2257.38  5166.3 2263.76
#Mann=3,-1,0
  4884.9    0.16       0  5005.1    0.07       0  5009.1    0.16       0
Bank Sta=5005.1,5009.1
Exp/Cntr=0.3,0.1

Type RM Length L Ch R = 1,1376,71,71,71
BEGIN DESCRIPTION:
Elm 56 1375.78
END DESCRIPTION:
XS GIS Cut Line= 3
      1518957.77      6760829.71      1519085.33      6760765.93
      1519215.52      6760685.21
#Sta/Elev= 30
  4858.0 2266.61  4872.3 2264.75  4877.9 2265.22  4894.7 2263.19  4900.3 2263.47
  4917.1 2260.21  4922.7 2260.25  4933.2 2258.02  4939.4 2255.33  4945.0 2254.86
  4955.5 2251.75  4977.9 2247.28  4984.1 2241.91  4995.6 2234.39  4995.9 2233.89
  4999.4 2233.89  4999.6 2234.39  5003.4 2234.39  5006.1 2238.38  5012.0 2241.70
  5021.5 2244.47  5042.8 2244.49  5064.0 2246.07  5079.4 2246.04  5085.3 2247.83
  5094.4 2247.73  5121.9 2255.14  5137.3 2260.71  5150.6 2263.09  5153.8 2263.09
#Mann=3,-1,0
  4858.0    0.16       0  4995.6    0.07       0  4999.6    0.16       0
Bank Sta=4995.6,4999.6
Exp/Cntr=0.3,0.1

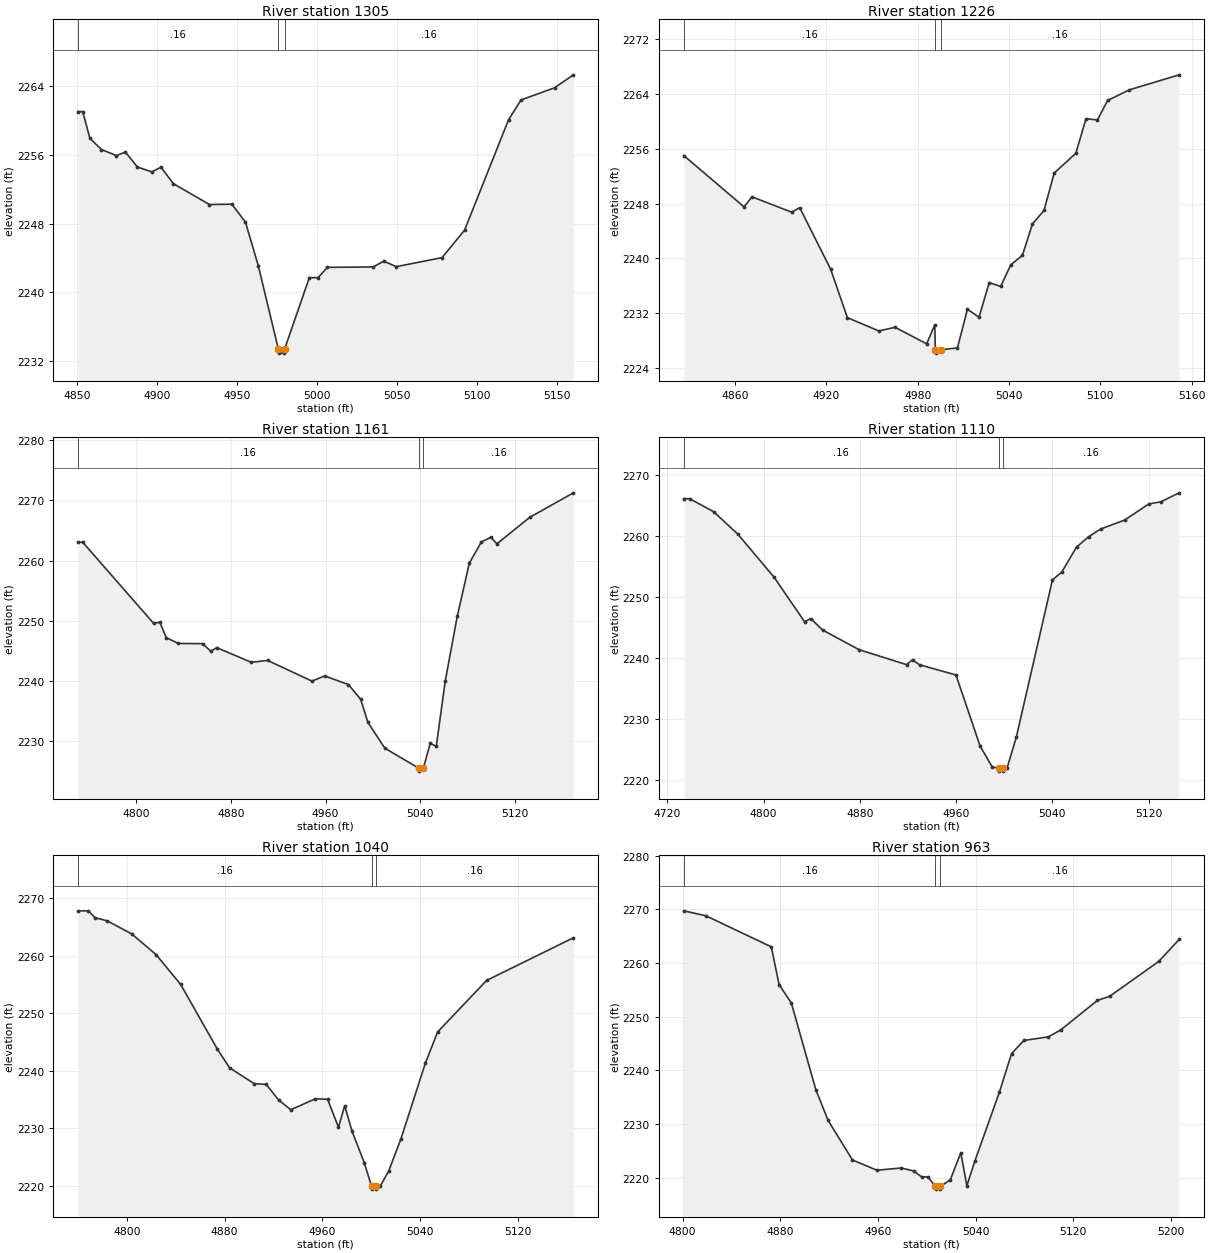
Type RM Length L Ch R = 1,1305,79,79,79
BEGIN DESCRIPTION:
Elm 56 1305.17
END DESCRIPTION:
XS GIS Cut Line= 3
      1519002.03      6760885.70      1519130.90      6760819.31
      1519257.20      6760713.85
#Sta/Elev= 30
  4850.8 2261.04  4853.7 2261.04  4858.2 2257.93  4865.4 2256.63  4874.8 2255.92
  4880.4 2256.33  4887.9 2254.59  4896.9 2254.03  4902.6 2254.57  4910.4 2252.65
  4932.9 2250.23  4946.9 2250.27  4955.4 2248.18  4963.4 2243.11  4975.9 2233.44
  4976.1 2232.94  4979.6 2232.94  4979.9 2233.44  4995.3 2241.72  5000.7 2241.72
  5006.6 2242.92  5035.2 2242.97  5041.8 2243.64  5049.6 2243.00  5078.2 2244.05
  5092.3 2247.25  5119.8 2260.11  5127.6 2262.40  5148.5 2263.81  5160.3 2265.32
#Mann=3,-1,0
  4850.8    0.16       0  4975.9    0.07       0  4979.9    0.16       0
Bank Sta=4975.9,4979.9
Exp/Cntr=0.3,0.1

Type RM Length L Ch R = 1,1226,65,65,65
BEGIN DESCRIPTION:
Elm 56 1225.61
END DESCRIPTION:
XS GIS Cut Line= 3
      1519043.63      6760896.15      1519203.82      6760841.45
      1519321.15      6760738.30
#Sta/Elev= 30
  4826.3 2255.03  4865.9 2247.52  4871.1 2248.99  4897.2 2246.75  4902.5 2247.40
  4922.8 2238.41  4933.8 2231.33  4954.5 2229.38  4965.1 2229.92  4985.9 2227.50
  4991.2 2230.26  4991.6 2226.64  4991.8 2226.14  4995.6 2226.64  5006.1 2226.90
  5012.7 2232.56  5020.3 2231.39  5027.0 2236.45  5034.5 2235.89  5041.2 2239.06
  5048.8 2240.43  5055.4 2245.03  5063.0 2247.00  5069.7 2252.47  5083.9 2255.35
  5090.6 2260.41  5098.1 2260.24  5104.8 2263.08  5119.0 2264.63  5151.8 2266.83
#Mann=3,-1,0
  4826.3    0.16       0  4991.6    0.07       0  4995.6    0.16       0
Bank Sta=4991.6,4995.6
Exp/Cntr=0.3,0.1

Type RM Length L Ch R = 1,1161,51,51,51
BEGIN DESCRIPTION:
Elm 56 1161.15
END DESCRIPTION:
XS GIS Cut Line= 3
      1519012.42      6760918.27      1519252.00      6760863.58
      1519421.25      6760829.99
#Sta/Elev= 30
  4751.0 2263.04  4754.9 2263.04  4814.8 2249.58  4820.0 2249.77  4825.5 2247.21
  4835.7 2246.25  4856.2 2246.21  4863.0 2244.96  4868.1 2245.55  4897.3 2243.12
  4911.1 2243.43  4948.5 2240.00  4959.2 2240.86  4979.3 2239.43  4989.6 2237.00
  4995.7 2233.19  5010.0 2228.88  5038.6 2225.57  5038.8 2225.07  5042.6 2225.57
  5048.4 2229.69  5053.5 2229.17  5061.0 2239.96  5071.2 2250.75  5081.4 2259.57
  5091.6 2263.10  5099.6 2263.85  5104.7 2262.77  5132.3 2267.15  5169.3 2271.23
#Mann=3,-1,0
  4751.0    0.16       0  5038.6    0.07       0  5042.6    0.16       0
Bank Sta=5038.6,5042.6
Exp/Cntr=0.3,0.1

Type RM Length L Ch R = 1,1110,70,70,70
BEGIN DESCRIPTION:
Elm 56 1109.74
END DESCRIPTION:
XS GIS Cut Line= 3
      1518990.27      6760944.32      1519254.60      6760914.37
      1519400.22      6760910.47
#Sta/Elev= 30
  4733.7 2266.08  4738.6 2266.08  4758.6 2263.94  4778.7 2260.26  4808.9 2253.20
  4834.1 2245.95  4839.2 2246.47  4849.2 2244.59  4879.4 2241.38  4918.8 2238.94
  4923.8 2239.73  4929.7 2238.91  4959.9 2237.25  4980.0 2225.61  4990.1 2222.19
  4995.4 2222.02  4995.7 2221.52  4999.2 2221.52  4999.4 2222.02  5002.4 2222.02
  5010.1 2227.11  5040.1 2252.80  5047.9 2254.09  5060.1 2258.16  5070.1 2259.85
  5080.2 2261.13  5100.2 2262.59  5120.2 2265.23  5130.2 2265.57  5145.4 2267.04
#Mann=3,-1,0
  4733.7    0.16       0  4995.4    0.07       0  4999.4    0.16       0
Bank Sta=4995.4,4999.4
Exp/Cntr=0.3,0.1

Type RM Length L Ch R = 1,1040,77,77,77
BEGIN DESCRIPTION:
Elm 56 1040.08
END DESCRIPTION:
XS GIS Cut Line= 3
      1518981.16      6760983.38      1519225.96      6760971.66
      1519386.07      6760970.36
#Sta/Elev= 30
  4760.1 2267.85  4768.5 2267.84  4774.0 2266.66  4784.0 2266.10  4804.0 2263.83
  4824.0 2260.21  4844.0 2255.04  4874.1 2243.75  4884.1 2240.50  4904.1 2237.77
  4914.1 2237.61  4924.1 2234.92  4934.1 2233.21  4954.2 2235.12  4964.2 2235.04
  4973.1 2230.15  4978.2 2233.91  4984.2 2229.48  4994.2 2223.99  5000.2 2219.89
  5000.4 2219.39  5003.9 2219.39  5004.2 2219.89  5007.2 2219.89  5014.2 2222.54
  5024.2 2228.13  5044.2 2241.33  5054.2 2246.75  5094.2 2255.72  5165.3 2263.16
#Mann=3,-1,0
  4760.1    0.16       0  5000.2    0.07       0  5004.2    0.16       0
Bank Sta=5000.2,5004.2
Exp/Cntr=0.3,0.1

Type RM Length L Ch R = 1,963,102,102,102
BEGIN DESCRIPTION:
Elm 56 962.87
END DESCRIPTION:
XS GIS Cut Line= 3
      1518966.88      6761021.14      1519163.46      6761026.35
      1519371.59      6761005.66
#Sta/Elev= 30
  4801.0 2269.72  4819.1 2268.80  4872.7 2263.01  4879.1 2255.96  4889.1 2252.56
  4909.2 2236.38  4919.2 2230.69  4939.2 2223.31  4959.2 2221.40  4979.2 2221.82
  4989.2 2221.27  4995.9 2220.17  5000.9 2220.17  5007.2 2218.38  5007.5 2217.88
  5011.0 2217.88  5011.2 2218.38  5019.3 2219.59  5027.9 2224.65  5032.9 2218.52
  5039.4 2223.08  5059.5 2235.90  5069.5 2243.12  5079.6 2245.57  5099.7 2246.25
  5109.7 2247.52  5139.9 2253.04  5149.9 2253.80  5190.1 2260.30  5206.8 2264.39
#Mann=3,-1,0
  4801.0    0.16       0  5007.2    0.07       0  5011.2    0.16       0
Bank Sta=5007.2,5011.2
Exp/Cntr=0.3,0.1

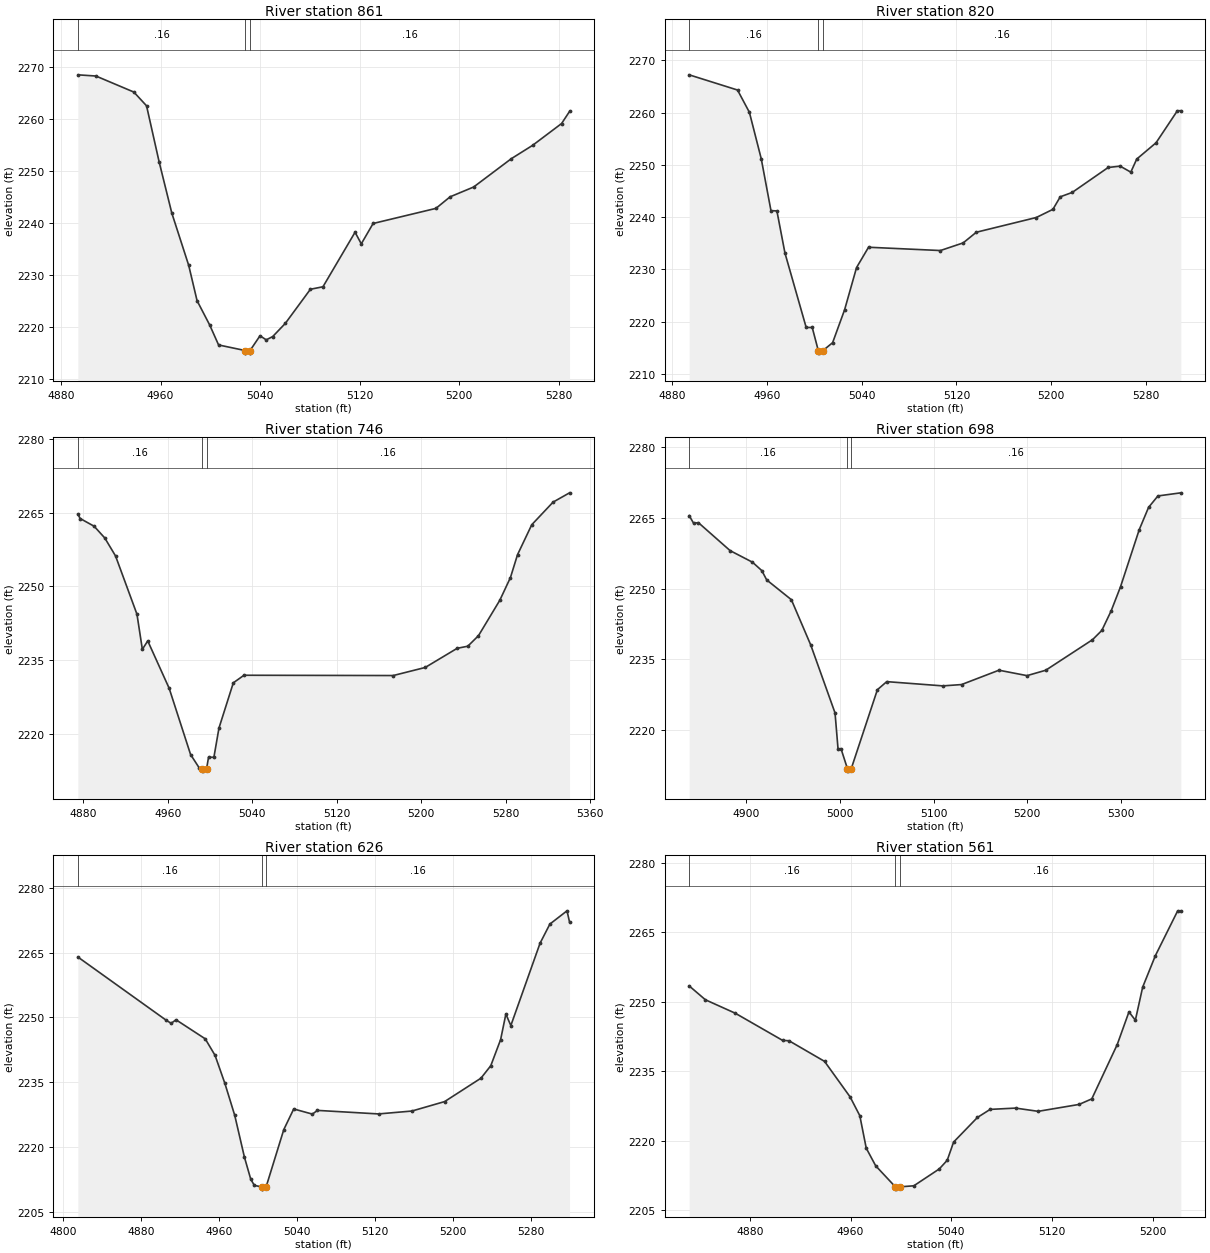
Type RM Length L Ch R = 1,861,41,41,41
BEGIN DESCRIPTION:
Elm 56 861.04
END DESCRIPTION:
XS GIS Cut Line= 3
      1518970.74      6761047.18      1519084.03      6761068.01
      1519361.32      6761029.14
#Sta/Elev= 30
  4893.5 2268.46  4908.0 2268.23  4938.5 2265.15  4948.7 2262.51  4958.8 2251.76
  4969.0 2241.92  4982.6 2231.87  4989.3 2225.10  4999.5 2220.41  5006.6 2216.60
  5027.9 2215.53  5028.1 2215.03  5031.6 2215.03  5031.9 2215.53  5039.9 2218.36
  5044.9 2217.58  5050.1 2218.21  5060.2 2220.73  5080.4 2227.29  5090.5 2227.77
  5116.3 2238.24  5121.3 2236.01  5130.8 2239.92  5181.3 2242.82  5192.7 2245.04
  5211.6 2246.92  5241.9 2252.36  5259.0 2254.92  5282.3 2259.11  5288.7 2261.43
#Mann=3,-1,0
  4893.5    0.16       0  5027.9    0.07       0  5031.9    0.16       0
Bank Sta=5027.9,5031.9
Exp/Cntr=0.3,0.1

Type RM Length L Ch R = 1,820,74,74,74
BEGIN DESCRIPTION:
Elm 56 820.23
END DESCRIPTION:
XS GIS Cut Line= 3
      1518964.24      6761105.77      1519065.80      6761101.87
      1519375.72      6761057.59
#Sta/Elev= 30
  4894.6 2267.24  4935.4 2264.33  4945.4 2260.07  4955.4 2251.18  4963.6 2241.25
  4968.6 2241.20  4975.4 2233.14  4993.3 2218.90  4998.4 2218.90  5003.5 2214.49
  5003.8 2213.99  5007.5 2214.49  5015.6 2215.99  5025.7 2222.28  5035.8 2230.37
  5045.9 2234.25  5106.5 2233.62  5125.7 2235.08  5136.8 2237.12  5187.4 2239.94
  5201.4 2241.50  5207.6 2243.90  5217.7 2244.74  5248.0 2249.51  5258.1 2249.77
  5267.1 2248.62  5272.1 2251.12  5288.4 2254.24  5306.4 2260.37  5309.3 2260.37
#Mann=3,-1,0
  4894.6    0.16       0  5003.5    0.07       0  5007.5    0.16       0
Bank Sta=5003.5,5007.5
Exp/Cntr=0.3,0.1

Type RM Length L Ch R = 1,746,48,48,48
BEGIN DESCRIPTION:
Elm 56 745.69
END DESCRIPTION:
XS GIS Cut Line= 3
      1518979.89      6761142.24      1519103.56      6761164.37
      1519440.40      6761116.25
#Sta/Elev= 30
  4874.7 2264.64  4876.9 2263.78  4890.1 2262.21  4900.2 2259.82  4910.4 2256.16
  4930.7 2244.30  4935.8 2237.16  4940.9 2238.88  4961.2 2229.24  4981.5 2215.76
  4989.6 2213.06  4992.7 2212.88  4992.9 2212.38  4996.7 2212.88  4998.5 2215.20
  5003.6 2215.20  5008.4 2221.15  5022.0 2230.35  5032.1 2231.89  5173.5 2231.83
  5203.8 2233.47  5234.1 2237.37  5244.2 2237.80  5254.3 2239.94  5274.5 2247.14
  5284.6 2251.77  5291.3 2256.42  5304.8 2262.52  5325.0 2267.12  5340.6 2269.01
#Mann=3,-1,0
  4874.7    0.16       0  4992.7    0.07       0  4996.7    0.16       0
Bank Sta=4992.7,4996.7
Exp/Cntr=0.3,0.1

Type RM Length L Ch R = 1,698,72,72,72
BEGIN DESCRIPTION:
Elm 56 698.42
END DESCRIPTION:
XS GIS Cut Line= 3
      1518949.88      6761255.52      1519106.16      6761211.24
      1519469.49      6761206.03
#Sta/Elev= 30
  4838.7 2265.47  4843.4 2263.87  4848.6 2263.97  4882.5 2258.05  4906.4 2255.60
  4916.4 2253.82  4921.6 2251.85  4948.0 2247.66  4968.7 2238.08  4994.7 2223.68
  4997.9 2216.10  5001.1 2216.10  5008.0 2211.86  5008.2 2211.36  5012.0 2211.86
  5040.0 2228.60  5050.0 2230.31  5110.0 2229.41  5130.0 2229.69  5170.0 2232.73
  5200.0 2231.58  5220.0 2232.72  5270.0 2239.18  5280.0 2241.15  5290.0 2245.30
  5300.0 2250.40  5320.0 2262.48  5330.0 2267.21  5340.0 2269.63  5364.5 2270.29
#Mann=3,-1,0
  4838.7    0.16       0  5008.0    0.07       0  5012.0    0.16       0
Bank Sta=5008,5012
Exp/Cntr=0.3,0.1

Type RM Length L Ch R = 1,626,65,65,65
BEGIN DESCRIPTION:
Elm 56 626.3
END DESCRIPTION:
XS GIS Cut Line= 3
      1518955.12      6761294.57      1519137.41      6761272.44
      1519454.96      6761222.99
#Sta/Elev= 30
  4815.1 2263.99  4905.6 2249.38  4910.9 2248.63  4915.9 2249.45  4945.9 2245.04
  4956.0 2241.21  4966.1 2234.71  4976.2 2227.32  4986.2 2217.60  4992.7 2212.49
  4996.4 2211.08  5004.4 2210.72  5004.7 2210.22  5008.4 2210.72  5026.6 2224.01
  5036.8 2228.79  5056.0 2227.60  5061.1 2228.46  5123.9 2227.64  5158.2 2228.31
  5191.8 2230.50  5229.1 2235.92  5239.2 2238.81  5249.3 2244.85  5254.7 2250.77
  5259.8 2248.11  5289.8 2267.18  5299.9 2271.62  5317.5 2274.69  5320.1 2272.09
#Mann=3,-1,0
  4815.1    0.16       0  5004.4    0.07       0  5008.4    0.16       0
Bank Sta=5004.4,5008.4
Exp/Cntr=0.3,0.1

Type RM Length L Ch R = 1,561,66,66,66
BEGIN DESCRIPTION:
Elm 56 561.168
END DESCRIPTION:
XS GIS Cut Line= 3
      1519018.89      6761345.36      1519184.88      6761318.15
      1519405.02      6761288.00
#Sta/Elev= 30
  4831.8 2253.43  4844.7 2250.43  4868.4 2247.53  4906.0 2241.66  4911.1 2241.58
  4939.3 2237.13  4959.6 2229.45  4967.3 2225.40  4972.4 2218.39  4979.9 2214.58
  4995.5 2210.04  4995.8 2209.54  4999.5 2210.04  5010.2 2210.26  5030.4 2213.90
  5036.7 2215.77  5041.8 2219.71  5060.7 2225.02  5070.8 2226.76  5091.0 2227.04
  5108.9 2226.34  5141.4 2227.83  5151.5 2229.03  5171.7 2240.76  5181.0 2247.81
  5186.1 2246.02  5191.9 2253.16  5202.0 2259.97  5219.7 2269.64  5222.2 2269.64
#Mann=3,-1,0
  4831.8    0.16       0  4995.5    0.07       0  4999.5    0.16       0
Bank Sta=4995.5,4999.5
Exp/Cntr=0.3,0.1

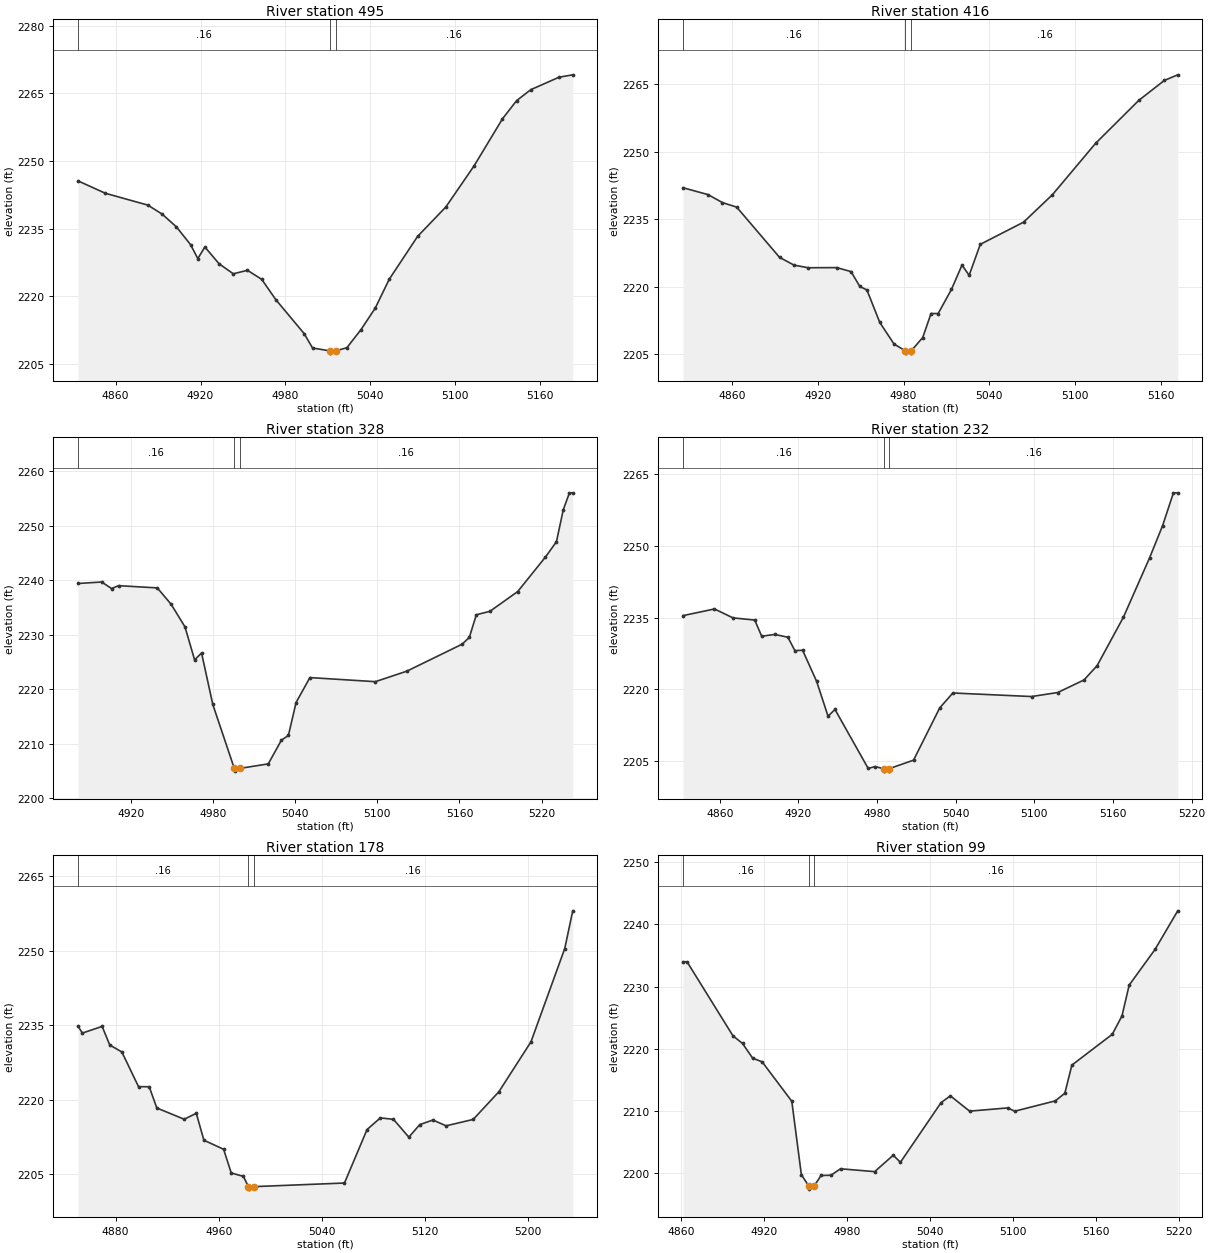
Type RM Length L Ch R = 1,495,79,79,79
BEGIN DESCRIPTION:
Elm 56 4762
END DESCRIPTION:
XS GIS Cut Line= 3
      1519065.82      6761381.81      1519231.52      6761364.50
      1519414.71      6761366.19
#Sta/Elev= 30
  4833.4 2245.58  4852.7 2242.83  4882.8 2240.20  4892.9 2238.20  4903.0 2235.36
  4913.0 2231.42  4918.1 2228.34  4923.1 2230.91  4933.1 2227.20  4943.2 2224.96
  4953.2 2225.74  4963.3 2223.73  4973.3 2219.20  4993.4 2211.65  4999.2 2208.50
  5011.5 2207.86  5011.7 2207.36  5015.5 2207.86  5023.5 2208.56  5033.5 2212.59
  5043.5 2217.32  5053.5 2223.78  5073.5 2233.26  5093.5 2239.80  5113.5 2248.94
  5133.5 2259.34  5143.5 2263.38  5153.5 2265.81  5173.5 2268.58  5183.2 2269.11
#Mann=3,-1,0
  4833.4    0.16       0  5011.5    0.07       0  5015.5    0.16       0
Bank Sta=5011.5,5015.5
Exp/Cntr=0.3,0.1

Type RM Length L Ch R = 1,416,88,88,88
BEGIN DESCRIPTION:
Elm 56 4761
END DESCRIPTION:
XS GIS Cut Line= 3
      1519077.51      6761424.78      1519251.63      6761436.26
      1519421.92      6761412.04
#Sta/Elev= 30
  4825.5 2242.03  4843.0 2240.50  4853.1 2238.73  4863.1 2237.72  4893.1 2226.57
  4903.2 2224.85  4913.2 2224.26  4933.2 2224.29  4943.2 2223.40  4949.3 2220.11
  4954.3 2219.33  4963.3 2212.12  4973.3 2207.32  4981.3 2205.80  4981.6 2205.30
  4985.1 2205.30  4985.3 2205.80  4993.4 2208.77  4999.2 2214.09  5004.2 2214.09
  5013.5 2219.45  5020.9 2224.85  5025.9 2222.58  5033.7 2229.46  5064.0 2234.38
  5084.2 2240.47  5114.5 2251.90  5144.8 2261.45  5162.6 2265.85  5172.0 2267.10
#Mann=3,-1,0
  4825.5    0.16       0  4981.3    0.07       0  4985.3    0.16       0
Bank Sta=4981.3,4985.3
Exp/Cntr=0.3,0.1

Type RM Length L Ch R = 1,328,96,96,96
BEGIN DESCRIPTION:
Elm 56 4760
END DESCRIPTION:
XS GIS Cut Line= 3
      1519087.94      6761488.59      1519204.81      6761508.20
      1519444.74      6761471.65
#Sta/Elev= 30
  4881.5 2239.38  4898.8 2239.65  4906.0 2238.45  4911.1 2238.98  4939.4 2238.57
  4949.5 2235.56  4959.6 2231.42  4966.6 2225.38  4971.7 2226.63  4979.9 2217.20
  4995.6 2205.48  4995.8 2204.98  4999.6 2205.48  5020.4 2206.31  5030.0 2210.66
  5035.1 2211.52  5040.7 2217.56  5050.8 2222.13  5098.6 2221.38  5121.6 2223.31
  5162.0 2228.26  5167.2 2229.50  5172.3 2233.64  5182.3 2234.29  5202.5 2237.90
  5222.7 2244.20  5230.8 2247.04  5235.8 2252.91  5240.3 2256.00  5242.7 2256.00
#Mann=3,-1,0
  4881.5    0.16       0  4995.6    0.07       0  4999.6    0.16       0
Bank Sta=4995.6,4999.6
Exp/Cntr=0.3,0.1

Type RM Length L Ch R = 1,232,54,54,54
BEGIN DESCRIPTION:
Elm 56 4759
END DESCRIPTION:
XS GIS Cut Line= 3
      1519089.22      6761534.15      1519247.17      6761591.40
      1519456.46      6761592.75
#Sta/Elev= 30
  4832.0 2235.40  4856.0 2236.79  4870.1 2234.93  4886.7 2234.47  4892.0 2231.10
  4902.0 2231.47  4912.0 2230.89  4917.3 2228.09  4923.2 2228.17  4933.9 2221.68
  4942.6 2214.41  4947.9 2215.81  4973.2 2203.51  4978.5 2203.89  4985.1 2203.44
  4985.3 2202.94  4988.8 2202.94  4989.1 2203.44  5007.8 2205.23  5027.8 2216.15
  5037.8 2219.25  5097.8 2218.51  5117.8 2219.35  5137.8 2221.97  5147.8 2224.95
  5167.8 2235.03  5187.8 2247.44  5197.8 2254.21  5206.0 2261.03  5209.3 2261.03
#Mann=3,-1,0
  4832.0    0.16       0  4985.1    0.07       0  4989.1    0.16       0
Bank Sta=4985.1,4989.1
Exp/Cntr=0.3,0.1

Type RM Length L Ch R = 1,178,79,79,79
BEGIN DESCRIPTION:
Elm 56 4758
END DESCRIPTION:
XS GIS Cut Line= 3
      1519085.30      6761552.37      1519211.56      6761631.67
      1519441.08      6761679.78
#Sta/Elev= 30
  4850.9 2234.78  4854.3 2233.41  4869.6 2234.75  4875.5 2231.00  4884.9 2229.60
  4897.8 2222.61  4906.1 2222.59  4912.0 2218.31  4933.2 2216.04  4942.6 2217.23
  4948.5 2211.81  4963.8 2209.98  4969.7 2205.21  4979.1 2204.52  4983.0 2202.45
  4983.3 2201.95  4987.0 2202.45  5057.5 2203.18  5075.0 2213.96  5085.3 2216.31
  5095.5 2216.02  5107.4 2212.43  5115.9 2214.96  5126.1 2215.88  5136.3 2214.71
  5157.3 2216.00  5177.2 2221.57  5202.1 2231.64  5228.3 2250.45  5234.5 2258.05
#Mann=3,-1,0
  4850.9    0.16       0  4983.0    0.07       0  4987.0    0.16       0
Bank Sta=4983,4987
Exp/Cntr=0.3,0.1

Type RM Length L Ch R = 1,99,57,57,57
BEGIN DESCRIPTION:
Elm 56 4756
END DESCRIPTION:
XS GIS Cut Line= 3
      1519063.18      6761588.83      1519158.41      6761689.40
      1519370.93      6761742.28
#Sta/Elev= 30
  4861.5 2234.00  4864.4 2234.00  4897.6 2222.10  4904.5 2220.88  4911.8 2218.52
  4918.7 2217.92  4940.1 2211.59  4947.0 2199.82  4952.3 2197.97  4952.5 2197.47
  4956.3 2197.97  4961.2 2199.66  4968.4 2199.70  4975.3 2200.74  5000.0 2200.28
  5013.4 2202.92  5018.6 2201.78  5048.0 2211.38  5054.7 2212.46  5068.6 2210.00
  5096.1 2210.52  5101.2 2209.99  5130.5 2211.65  5137.4 2212.87  5142.5 2217.40
  5171.7 2222.35  5178.7 2225.30  5183.9 2230.25  5202.6 2235.99  5219.0 2242.19
#Mann=3,-1,0
  4861.5    0.16       0  4952.3    0.07       0  4956.3    0.16       0
Bank Sta=4952.3,4956.3
Exp/Cntr=0.3,0.1

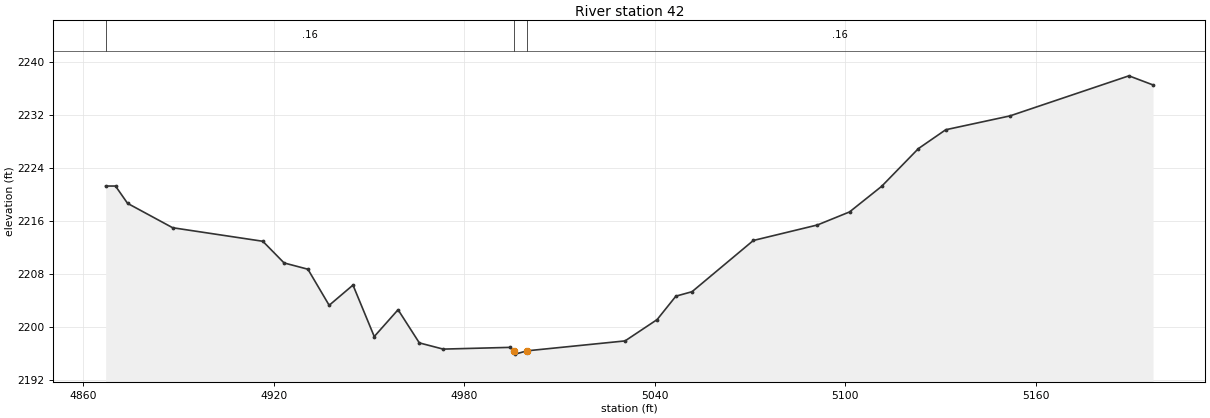
Type RM Length L Ch R = 1,42,0,0,0
BEGIN DESCRIPTION:
Elm 56 4757
END DESCRIPTION:
XS GIS Cut Line= 3
      1519065.82      6761647.46      1519154.68      6761746.42
      1519349.67      6761773.74
#Sta/Elev= 30
  4867.0 2221.28  4870.1 2221.28  4873.9 2218.66  4888.1 2214.97  4916.5 2212.92
  4923.2 2209.64  4930.7 2208.69  4937.4 2203.23  4944.9 2206.29  4951.6 2198.50
  4959.1 2202.56  4965.8 2197.54  4973.3 2196.60  4994.2 2196.86  4995.7 2196.34
  4996.0 2195.84  4999.7 2196.34  5030.6 2197.84  5040.7 2201.07  5046.6 2204.61
  5051.7 2205.29  5071.0 2213.04  5091.2 2215.39  5101.3 2217.36  5111.4 2221.23
  5123.0 2226.95  5131.6 2229.80  5151.8 2231.89  5189.3 2237.96  5196.9 2236.58
#Mann=3,-1,0
  4867.0    0.16       0  4995.7    0.07       0  4999.7    0.16       0
Bank Sta=4995.7,4999.7
Exp/Cntr=0.3,0.1

Chan Stop Cuts=-1