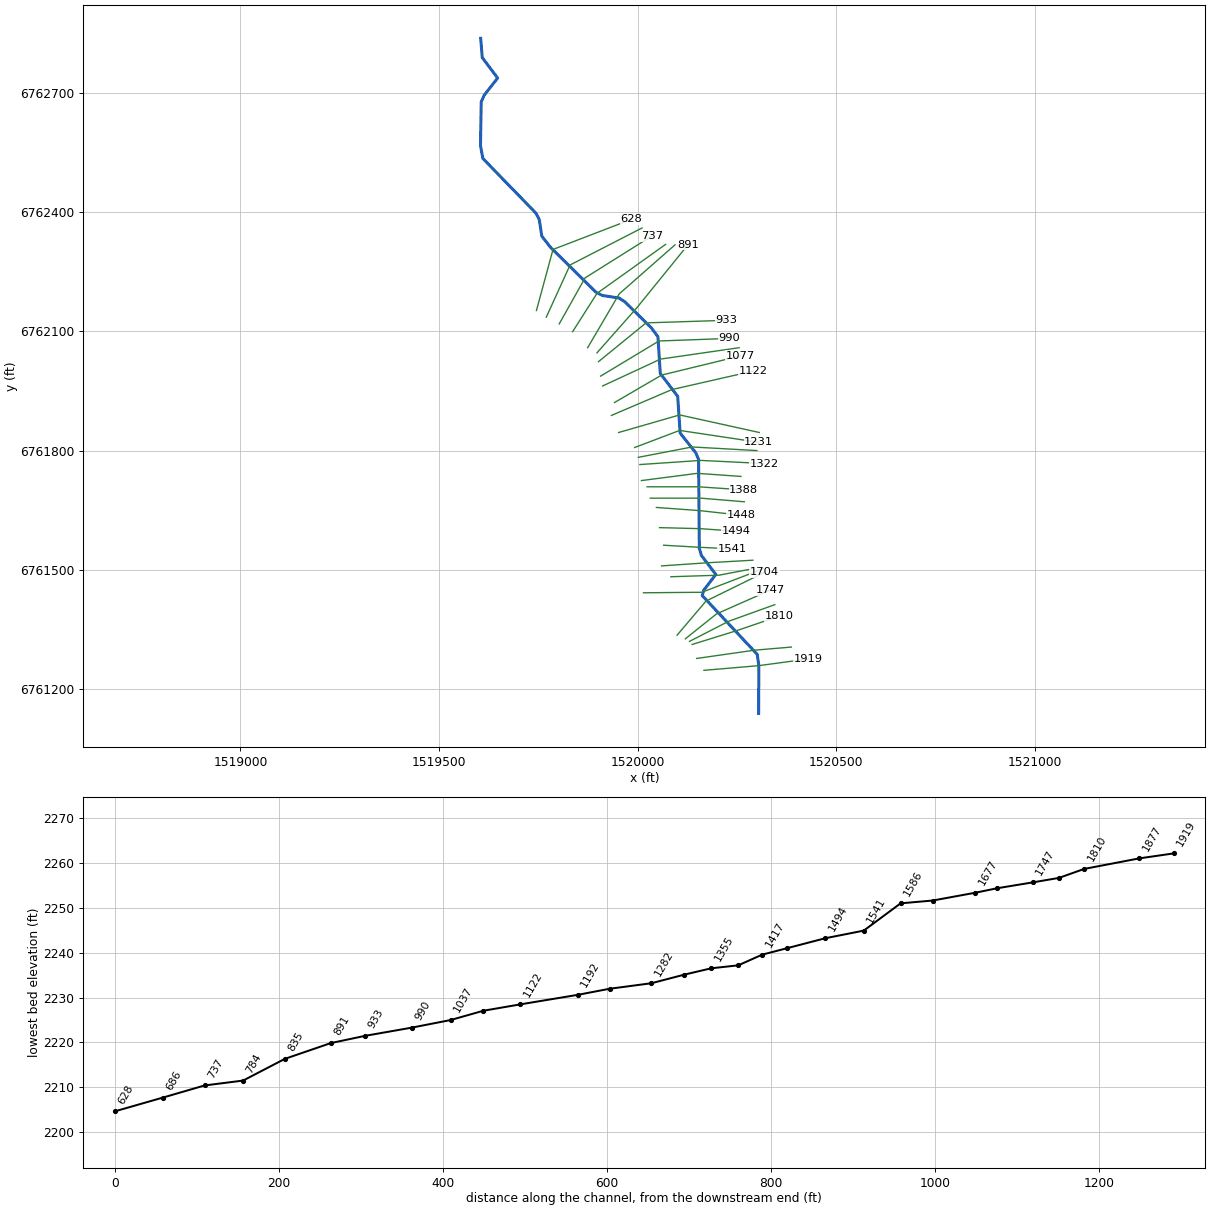
--- Elm 57.prj (project) ---

Proj Title=Elm 57 Base Level Engineering
Current Plan=p01
Default Exp/Contr=0.3,0.1
English Units
Geom File=g01
Flow File=f01
Plan File=p01
BEGIN DESCRIPTION:
Elm 57
END DESCRIPTION:

--- Elm 57.p01 (plan) ---

Plan Title=Multiple Run
Short Identifier=Multiple
Geom File=g01
Flow File=f01
Subcritical Flow
K Sum by GR= 0
Std Step Tol= 0.01
Critical Tol= 0.01
Num of Std Step Trials= 20
Max Error Tol= 0.3
Flow Tol Ratio= 0.001
Split Flow NTrial= 30
Split Flow Tol= 0.02
Split Flow Ratio= 0.02
Log Output Level= 0
Friction Slope Method= 1
Unsteady Friction Slope Method= 2
Unsteady Bridges Friction Slope Method= 1
Parabolic Critical Depth
Global Vel Dist=  1 , 1 , 1
Global Log Level= 0
CheckData=True
Encroach Param= -1, 0, 0, 0
BEGIN DESCRIPTION:
Multiple Run
END DESCRIPTION:

--- Elm 57.f01 (steady flow) ---

Flow Title=Multiple
Number of Profiles=7
Profile Names=10-year,25-year,50-year,1pct_min,100-year,1pct_plu,500-year
River Rch & RM= Elm 57,Reach-1,1919
      87     115     138     103     165     227     238
Boundary for River Rch & Prof#=Elm 57,Reach-1,1
Up Type=0
Dn Type=3
Dn Slope=0.005
Boundary for River Rch & Prof#=Elm 57,Reach-1,2
Up Type=0
Dn Type=3
Dn Slope=0.005
Boundary for River Rch & Prof#=Elm 57,Reach-1,3
Up Type=0
Dn Type=3
Dn Slope=0.005
Boundary for River Rch & Prof#=Elm 57,Reach-1,4
Up Type=0
Dn Type=3
Dn Slope=0.005
Boundary for River Rch & Prof#=Elm 57,Reach-1,5
Up Type=0
Dn Type=3
Dn Slope=0.005
Boundary for River Rch & Prof#=Elm 57,Reach-1,6
Up Type=0
Dn Type=3
Dn Slope=0.005
Boundary for River Rch & Prof#=Elm 57,Reach-1,7
Up Type=0
Dn Type=3
Dn Slope=0.005

--- Elm 57.g01 (geometry) ---

Geom Title=Existing Conditions

River Reach=Elm 57,Reach-1
Reach XY= 30
      1520305.00      6761138.00      1520305.52      6761258.21
      1520301.50      6761286.55      1520162.99      6761434.66
      1520166.68      6761447.99      1520197.19      6761487.90
      1520161.00      6761535.55      1520155.65      6761553.16
      1520153.78      6761777.50      1520146.86      6761794.06
      1520107.36      6761843.98      1520101.15      6761936.40
      1520057.36      6761993.98      1520051.39      6762086.52
      1520035.39      6762108.20      1519968.24      6762174.38
      1519953.37      6762184.03      1519911.05      6762190.54
      1519895.32      6762198.78      1519781.30      6762311.18
      1519758.98      6762339.65      1519752.46      6762381.95
      1519744.22      6762397.68      1519610.45      6762535.55
      1519604.54      6762567.83      1519606.36      6762677.56
      1519613.43      6762694.19      1519647.69      6762738.04
      1519609.00      6762789.36      1519605.00      6762838.00

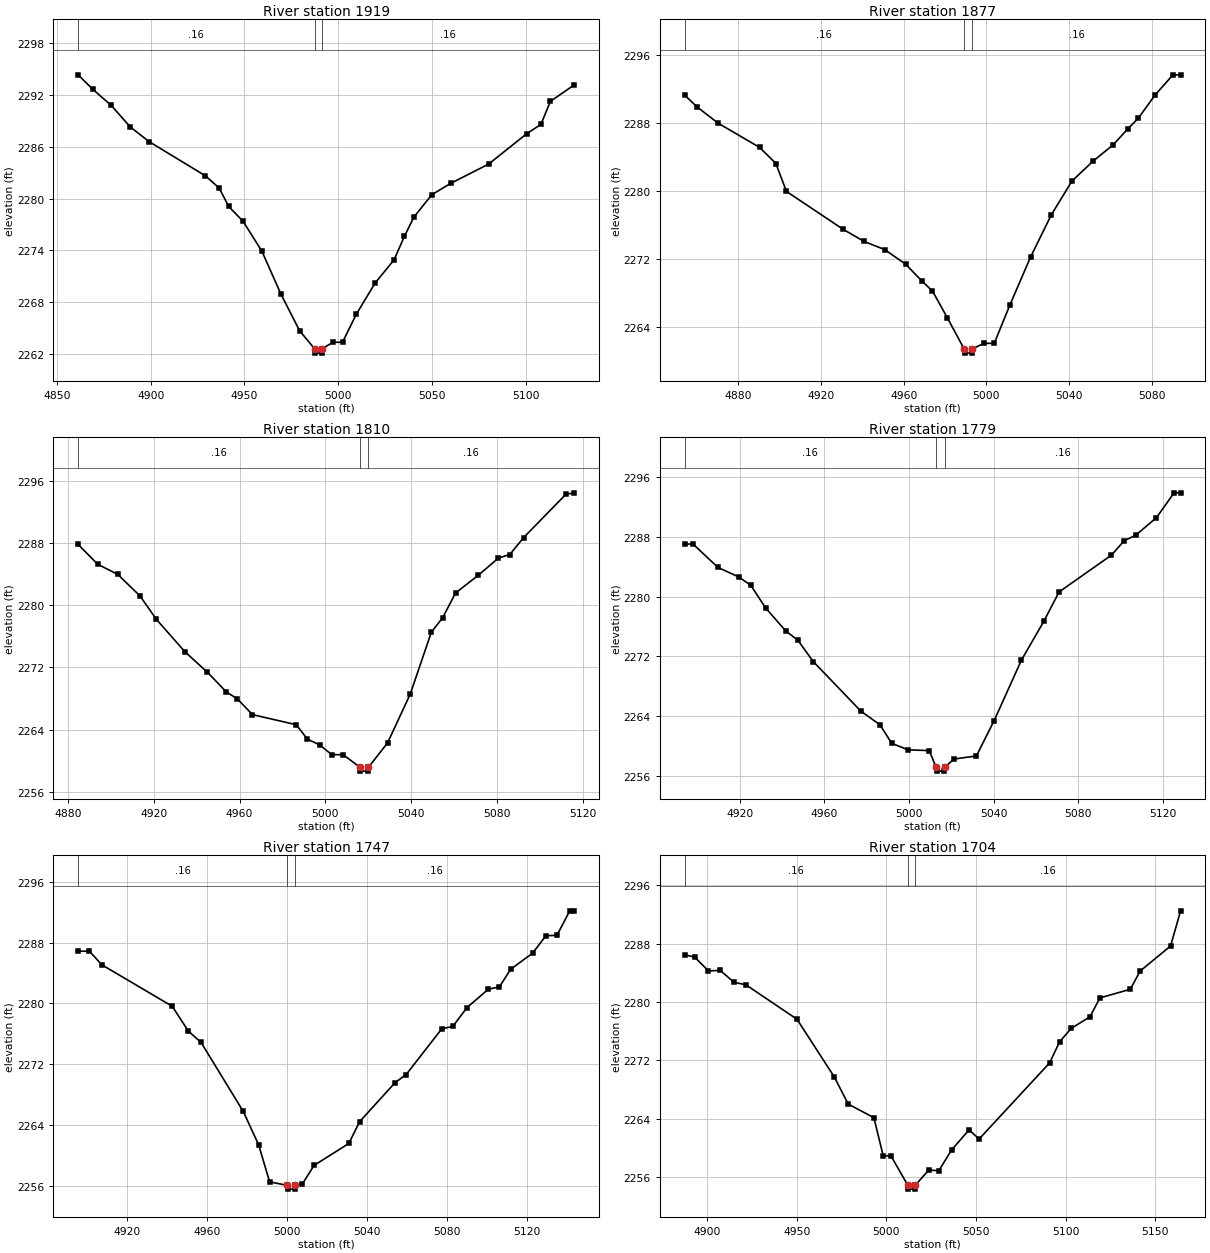
Type RM Length L Ch R = 1,1919,42,42,42
BEGIN DESCRIPTION:
Elm 57 1918.903
END DESCRIPTION:
XS GIS Cut Line= 3
      1520167.32      6761246.39      1520305.52      6761258.21
      1520430.19      6761275.02
#Sta/Elev= 30
  4861.3 2294.34  4869.0 2292.69  4879.0 2290.79  4889.1 2288.31  4899.1 2286.61
  4929.2 2282.64  4936.5 2281.23  4941.6 2279.09  4949.3 2277.36  4959.3 2273.91
  4969.4 2268.96  4979.4 2264.70  4987.4 2262.60  4987.7 2262.10  4991.2 2262.10
  4991.4 2262.60  4997.2 2263.36  5002.3 2263.36  5009.6 2266.59  5019.7 2270.23
  5029.8 2272.91  5035.3 2275.64  5040.4 2277.87  5049.9 2280.45  5060.0 2281.77
  5080.2 2284.00  5100.4 2287.50  5108.1 2288.60  5113.1 2291.26  5125.8 2293.17
#Mann=3,-1,0
  4861.3    0.16       0  4987.4    0.07       0  4991.4    0.16       0
Bank Sta=4987.4,4991.4
Exp/Cntr=0.3,0.1

Type RM Length L Ch R = 1,1877,67,67,67
BEGIN DESCRIPTION:
Elm 57 1877.25
END DESCRIPTION:
XS GIS Cut Line= 3
      1520149.08      6761276.34      1520294.97      6761297.18
      1520387.37      6761304.99
#Sta/Elev= 30
  4853.9 2291.26  4859.9 2289.88  4870.0 2287.98  4890.2 2285.12  4898.1 2283.23
  4903.2 2279.96  4930.6 2275.52  4940.7 2274.10  4950.8 2273.13  4960.9 2271.42
  4968.8 2269.44  4973.9 2268.27  4981.1 2265.13  4989.2 2261.49  4989.4 2260.99
  4992.9 2260.99  4993.2 2261.49  4998.8 2262.14  5003.8 2262.14  5011.3 2266.60
  5021.4 2272.27  5031.4 2277.20  5041.4 2281.17  5051.5 2283.48  5061.5 2285.45
  5068.5 2287.31  5073.5 2288.53  5081.6 2291.25  5090.3 2293.63  5094.0 2293.63
#Mann=3,-1,0
  4853.9    0.16       0  4989.2    0.07       0  4993.2    0.16       0
Bank Sta=4989.2,4993.2
Exp/Cntr=0.3,0.1

Type RM Length L Ch R = 1,1810,31,31,31
BEGIN DESCRIPTION:
Elm 57 1810.01
END DESCRIPTION:
XS GIS Cut Line= 3
      1520137.37      6761311.49      1520250.70      6761346.66
      1520357.30      6761383.06
#Sta/Elev= 30
  4884.7 2287.85  4893.9 2285.29  4903.2 2283.99  4913.6 2281.21  4921.2 2278.20
  4934.6 2274.00  4945.0 2271.39  4953.8 2268.86  4959.0 2267.95  4966.0 2265.93
  4986.4 2264.63  4991.6 2262.78  4997.4 2262.02  5003.0 2260.77  5008.3 2260.77
  5016.1 2259.15  5016.3 2258.65  5019.8 2258.65  5020.1 2259.15  5029.0 2262.29
  5039.6 2268.59  5049.4 2276.54  5054.7 2278.42  5060.7 2281.60  5071.3 2283.88
  5080.7 2286.10  5086.0 2286.55  5092.4 2288.72  5112.1 2294.30  5116.0 2294.50
#Mann=3,-1,0
  4884.7    0.16       0  5016.1    0.07       0  5020.1    0.16       0
Bank Sta=5016.1,5020.1
Exp/Cntr=0.3,0.1

Type RM Length L Ch R = 1,1779,32,32,32
BEGIN DESCRIPTION:
Elm 57 1778.67
END DESCRIPTION:
XS GIS Cut Line= 3
      1520130.90      6761319.31      1520229.86      6761370.10
      1520345.77      6761411.77
#Sta/Elev= 30
  4894.0 2287.06  4898.0 2287.06  4909.8 2283.92  4919.7 2282.64  4925.3 2281.53
  4932.3 2278.50  4941.9 2275.39  4947.5 2274.19  4954.8 2271.32  4977.3 2264.68
  4986.3 2262.86  4991.9 2260.36  4999.7 2259.49  5009.6 2259.39  5012.9 2257.14
  5013.2 2256.64  5016.7 2256.64  5016.9 2257.14  5021.3 2258.26  5031.9 2258.67
  5040.3 2263.42  5053.2 2271.52  5063.8 2276.73  5071.0 2280.65  5095.7 2285.57
  5101.8 2287.52  5107.1 2288.22  5117.0 2290.60  5125.3 2293.92  5128.4 2293.92
#Mann=3,-1,0
  4894.0    0.16       0  5012.9    0.07       0  5016.9    0.16       0
Bank Sta=5012.9,5016.9
Exp/Cntr=0.3,0.1

Type RM Length L Ch R = 1,1747,43,43,43
BEGIN DESCRIPTION:
Elm 57 1746.85
END DESCRIPTION:
XS GIS Cut Line= 3
      1520120.48      6761325.82      1520198.61      6761388.32
      1520334.01      6761448.21
#Sta/Elev= 30
  4895.6 2286.86  4901.3 2286.86  4907.4 2285.09  4942.7 2279.63  4950.7 2276.39
  4957.1 2274.89  4978.2 2265.84  4985.9 2261.45  4991.4 2256.59  5000.2 2256.14
  5000.4 2255.64  5003.9 2255.64  5004.2 2256.14  5007.7 2256.29  5013.6 2258.75
  5031.0 2261.63  5036.4 2264.49  5054.2 2269.63  5059.7 2270.68  5077.5 2276.68
  5083.0 2276.99  5090.1 2279.46  5100.8 2281.88  5106.3 2282.18  5112.0 2284.50
  5122.9 2286.60  5129.6 2288.90  5135.1 2288.94  5141.5 2292.16  5143.7 2292.16
#Mann=3,-1,0
  4895.6    0.16       0  5000.2    0.07       0  5004.2    0.16       0
Bank Sta=5000.2,5004.2
Exp/Cntr=0.3,0.1

Type RM Length L Ch R = 1,1704,27,27,27
BEGIN DESCRIPTION:
Elm 57 1703.8
END DESCRIPTION:
XS GIS Cut Line= 3
      1520099.63      6761334.91      1520172.57      6761420.88
      1520319.73      6761493.17
#Sta/Elev= 30
  4887.4 2286.48  4893.0 2286.17  4900.7 2284.28  4907.3 2284.33  4915.0 2282.71
  4921.6 2282.37  4950.1 2277.65  4971.0 2269.70  4978.7 2266.01  4993.0 2264.15
  4998.2 2258.92  5002.5 2258.92  5012.0 2254.85  5012.2 2254.35  5015.7 2254.35
  5016.0 2254.85  5023.6 2256.97  5029.2 2256.87  5036.3 2259.70  5046.1 2262.48
  5051.7 2261.22  5091.0 2271.65  5096.6 2274.55  5103.1 2276.40  5113.5 2277.97
  5119.1 2280.57  5136.0 2281.75  5141.6 2284.27  5158.5 2287.69  5164.1 2292.51
#Mann=3,-1,0
  4887.4    0.16       0  5012.0    0.07       0  5016.0    0.16       0
Bank Sta=5012,5016
Exp/Cntr=0.3,0.1

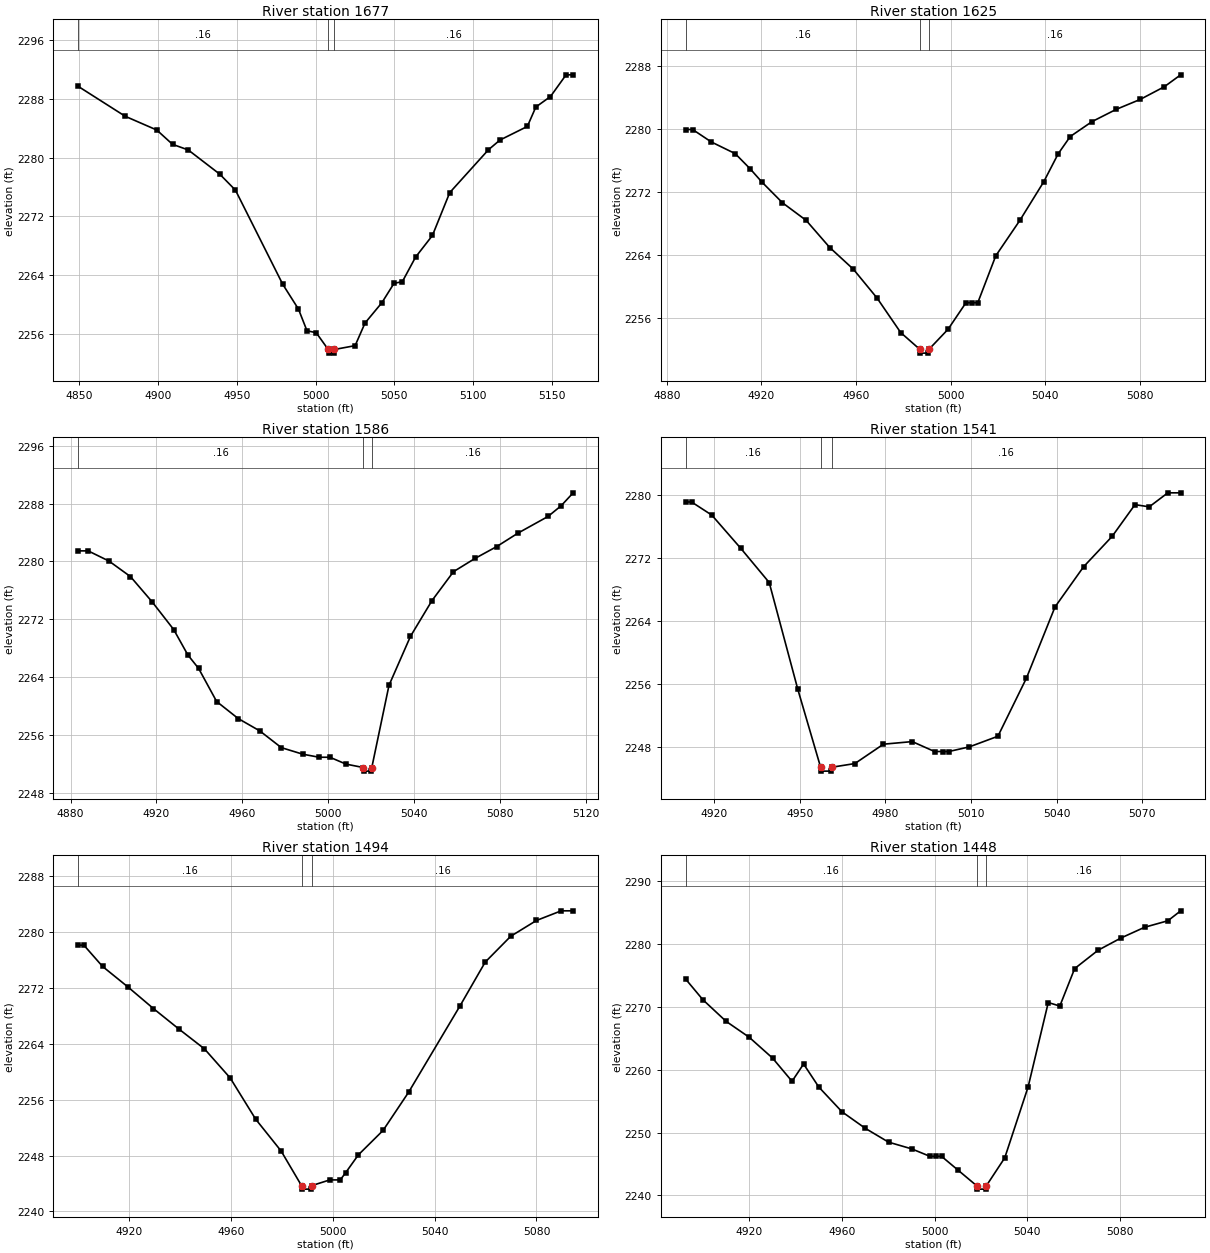
Type RM Length L Ch R = 1,1677,52,52,52
BEGIN DESCRIPTION:
Elm 57 1676.91
END DESCRIPTION:
XS GIS Cut Line= 3
      1520015.04      6761441.71      1520162.15      6761443.01
      1520318.44      6761502.92
#Sta/Elev= 30
  4849.1 2289.75  4879.1 2285.65  4899.1 2283.78  4909.1 2281.83  4919.1 2281.06
  4939.1 2277.76  4949.1 2275.57  4979.1 2262.74  4989.1 2259.35  4994.5 2256.40
  5000.4 2256.12  5008.0 2253.84  5008.2 2253.34  5011.7 2253.34  5012.0 2253.84
  5025.1 2254.36  5031.4 2257.45  5042.1 2260.22  5049.8 2262.86  5055.1 2263.09
  5063.5 2266.44  5074.2 2269.39  5085.2 2275.24  5109.8 2281.09  5117.1 2282.41
  5134.5 2284.27  5139.9 2286.92  5149.2 2288.35  5159.1 2291.31  5163.6 2291.31
#Mann=3,-1,0
  4849.1    0.16       0  5008.0    0.07       0  5012.0    0.16       0
Bank Sta=5008,5012
Exp/Cntr=0.3,0.1

Type RM Length L Ch R = 1,1625,39,39,39
BEGIN DESCRIPTION:
Elm 57 1624.99
END DESCRIPTION:
XS GIS Cut Line= 3
      1520084.06      6761482.08      1520205.12      6761485.98
      1520291.83      6761502.56
#Sta/Elev= 30
  4887.9 2279.98  4890.9 2279.98  4898.8 2278.40  4908.9 2276.92  4915.2 2275.00
  4920.2 2273.31  4928.9 2270.68  4938.9 2268.45  4948.9 2265.00  4958.9 2262.24
  4968.9 2258.59  4978.9 2254.21  4986.9 2252.10  4987.1 2251.60  4990.6 2251.60
  4990.9 2252.10  4998.9 2254.62  5006.5 2258.00  5009.0 2258.00  5011.5 2258.00
  5019.1 2263.95  5029.3 2268.45  5039.4 2273.35  5045.5 2276.90  5050.6 2279.09
  5059.8 2280.98  5070.0 2282.53  5080.2 2283.80  5090.4 2285.41  5097.3 2286.92
#Mann=3,-1,0
  4887.9    0.16       0  4986.9    0.07       0  4990.9    0.16       0
Bank Sta=4986.9,4990.9
Exp/Cntr=0.3,0.1

Type RM Length L Ch R = 1,1586,45,45,45
BEGIN DESCRIPTION:
Elm 57 1586.43
END DESCRIPTION:
XS GIS Cut Line= 3
      1520060.63      6761509.42      1520175.17      6761517.23
      1520290.58      6761523.71
#Sta/Elev= 30
  4883.5 2281.45  4888.2 2281.45  4897.9 2280.04  4907.9 2277.89  4918.0 2274.39
  4928.0 2270.57  4934.6 2267.05  4939.6 2265.19  4948.0 2260.61  4958.0 2258.26
  4968.1 2256.54  4978.1 2254.23  4988.1 2253.32  4995.7 2252.90  5000.7 2252.90
  5008.2 2251.95  5016.2 2251.48  5016.4 2250.98  5019.9 2250.98  5020.2 2251.48
  5028.2 2262.85  5038.2 2269.63  5048.2 2274.57  5058.2 2278.57  5068.2 2280.40
  5078.3 2282.04  5088.3 2283.92  5102.2 2286.21  5108.3 2287.69  5113.9 2289.48
#Mann=3,-1,0
  4883.5    0.16       0  5016.2    0.07       0  5020.2    0.16       0
Bank Sta=5016.2,5020.2
Exp/Cntr=0.3,0.1

Type RM Length L Ch R = 1,1541,47,47,47
BEGIN DESCRIPTION:
Elm 57 1540.73
END DESCRIPTION:
XS GIS Cut Line= 3
      1520065.78      6761561.50      1520155.64      6761556.29
      1520238.93      6761552.39
#Sta/Elev= 26
  4910.0 2279.08  4912.1 2279.08  4919.2 2277.41  4929.3 2273.21  4939.3 2268.85
  4949.3 2255.31  4957.3 2245.40  4957.6 2244.90  4961.1 2244.90  4961.3 2245.40
  4969.3 2245.86  4979.3 2248.32  4989.4 2248.65  4997.2 2247.39  5000.0 2247.39
  5002.2 2247.39  5009.4 2247.98  5019.4 2249.33  5029.4 2256.72  5039.4 2265.75
  5049.4 2270.85  5059.4 2274.71  5067.4 2278.74  5072.4 2278.46  5078.9 2280.24
  5083.4 2280.24
#Mann=3,-1,0
  4910.0    0.16       0  4957.3    0.07       0  4961.3    0.16       0
Bank Sta=4957.3,4961.3
Exp/Cntr=0.3,0.1

Type RM Length L Ch R = 1,1494,46,46,46
BEGIN DESCRIPTION:
Elm 57 1493.78
END DESCRIPTION:
XS GIS Cut Line= 3
      1520055.37      6761605.77      1520158.25      6761603.17
      1520249.40      6761596.66
#Sta/Elev= 26
  4900.1 2278.10  4902.4 2278.10  4909.7 2275.07  4919.7 2272.12  4929.7 2269.03
  4939.7 2266.10  4949.7 2263.27  4959.8 2259.11  4969.8 2253.21  4979.8 2248.65
  4987.8 2243.70  4988.0 2243.20  4991.5 2243.20  4991.8 2243.70  4998.9 2244.52
  5003.0 2244.52  5005.1 2245.54  5010.1 2248.10  5019.8 2251.60  5029.8 2257.05
  5049.9 2269.36  5059.9 2275.69  5069.9 2279.38  5080.0 2281.64  5089.7 2283.02
  5094.4 2283.02
#Mann=3,-1,0
  4900.1    0.16       0  4987.8    0.07       0  4991.8    0.16       0
Bank Sta=4987.8,4991.8
Exp/Cntr=0.3,0.1

Type RM Length L Ch R = 1,1448,31,31,31
BEGIN DESCRIPTION:
Elm 57 1448.22
END DESCRIPTION:
XS GIS Cut Line= 3
      1520047.53      6761656.56      1520155.64      6761648.74
      1520260.51      6761637.09
#Sta/Elev= 30
  4892.4 2274.47  4899.9 2271.16  4909.9 2267.73  4919.9 2265.19  4930.0 2261.87
  4938.4 2258.18  4943.4 2260.93  4950.0 2257.25  4960.0 2253.32  4970.1 2250.68
  4980.1 2248.49  4990.1 2247.42  4998.0 2246.23  5000.8 2246.23  5003.0 2246.23
  5010.2 2244.01  5018.3 2241.51  5018.5 2241.01  5022.0 2241.01  5022.3 2241.51
  5030.3 2245.99  5040.4 2257.29  5049.1 2270.72  5054.1 2270.16  5060.5 2276.12
  5070.6 2279.04  5080.6 2281.01  5090.7 2282.70  5100.8 2283.74  5106.3 2285.32
#Mann=3,-1,0
  4892.4    0.16       0  5018.3    0.07       0  5022.3    0.16       0
Bank Sta=5018.3,5022.3
Exp/Cntr=0.3,0.1

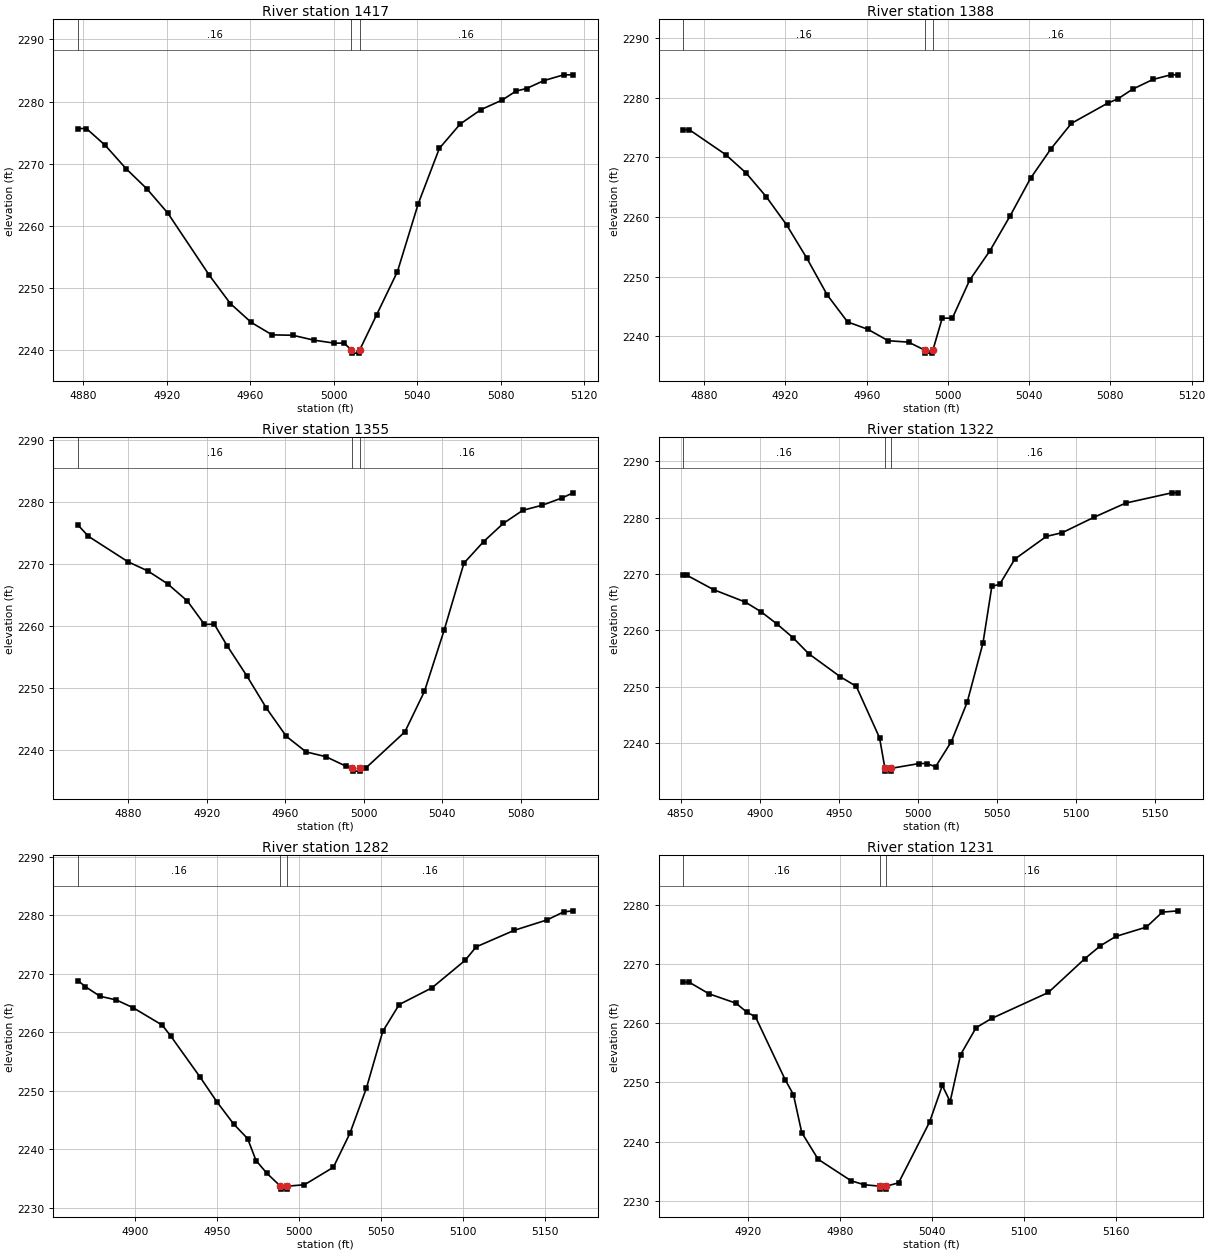
Type RM Length L Ch R = 1,1417,29,29,29
BEGIN DESCRIPTION:
Elm 57 1417.03
END DESCRIPTION:
XS GIS Cut Line= 3
      1520032.00      6761679.99      1520159.55      6761679.99
      1520268.92      6761670.88
#Sta/Elev= 30
  4877.4 2275.67  4881.4 2275.67  4890.4 2272.98  4900.4 2269.22  4910.4 2265.97
  4920.4 2262.08  4940.4 2252.03  4950.4 2247.52  4960.4 2244.49  4970.4 2242.48
  4980.4 2242.41  4990.4 2241.63  5000.2 2241.15  5005.0 2241.15  5008.4 2240.04
  5008.7 2239.54  5012.2 2239.54  5012.4 2240.04  5020.5 2245.68  5030.5 2252.65
  5040.5 2263.59  5050.6 2272.48  5060.6 2276.40  5070.6 2278.72  5080.7 2280.25
  5087.4 2281.70  5092.4 2282.11  5100.7 2283.38  5110.2 2284.31  5114.7 2284.31
#Mann=3,-1,0
  4877.4    0.16       0  5008.4    0.07       0  5012.4    0.16       0
Bank Sta=5008.4,5012.4
Exp/Cntr=0.3,0.1

Type RM Length L Ch R = 1,1388,33,33,33
BEGIN DESCRIPTION:
Elm 57 1388.47
END DESCRIPTION:
XS GIS Cut Line= 3
      1520024.16      6761708.64      1520153.04      6761708.64
      1520267.59      6761700.83
#Sta/Elev= 30
  4869.8 2274.60  4872.7 2274.60  4890.6 2270.43  4900.6 2267.37  4910.6 2263.36
  4920.6 2258.65  4930.6 2253.04  4940.6 2246.91  4950.6 2242.40  4960.6 2241.16
  4970.6 2239.25  4980.6 2239.01  4988.6 2237.67  4988.9 2237.17  4992.4 2237.17
  4992.6 2237.67  4997.2 2243.03  5002.2 2243.03  5010.7 2249.40  5020.7 2254.33
  5030.7 2260.21  5040.7 2266.48  5050.8 2271.44  5060.8 2275.67  5078.7 2279.06
  5083.7 2279.78  5090.9 2281.39  5100.9 2283.02  5109.7 2283.80  5113.5 2283.80
#Mann=3,-1,0
  4869.8    0.16       0  4988.6    0.07       0  4992.6    0.16       0
Bank Sta=4988.6,4992.6
Exp/Cntr=0.3,0.1

Type RM Length L Ch R = 1,1355,33,33,33
BEGIN DESCRIPTION:
Elm 57 1354.78
END DESCRIPTION:
XS GIS Cut Line= 3
      1520009.76      6761724.26      1520150.44      6761742.49
      1520260.51      6761734.72
#Sta/Elev= 30
  4854.5 2276.22  4859.8 2274.41  4879.9 2270.31  4890.0 2268.83  4900.1 2266.75
  4910.2 2263.97  4918.9 2260.19  4923.9 2260.23  4930.4 2256.78  4940.5 2251.88
  4950.5 2246.66  4960.6 2242.13  4970.7 2239.61  4980.8 2238.84  4990.9 2237.32
  4994.1 2237.01  4994.4 2236.51  4997.9 2236.51  4998.1 2237.01  5001.1 2237.01
  5021.0 2242.84  5031.0 2249.40  5041.0 2259.24  5051.1 2270.08  5061.1 2273.55
  5071.1 2276.48  5081.1 2278.61  5091.1 2279.44  5101.2 2280.62  5106.7 2281.43
#Mann=3,-1,0
  4854.5    0.16       0  4994.1    0.07       0  4998.1    0.16       0
Bank Sta=4994.1,4998.1
Exp/Cntr=0.3,0.1

Type RM Length L Ch R = 1,1322,40,40,40
BEGIN DESCRIPTION:
Elm 57 1322.36
END DESCRIPTION:
XS GIS Cut Line= 3
      1520005.95      6761764.63      1520159.55      6761775.04
      1520318.40      6761767.23
#Sta/Elev= 30
  4851.8 2269.80  4853.8 2269.80  4870.9 2267.22  4890.9 2265.03  4901.0 2263.29
  4911.0 2261.13  4921.0 2258.74  4931.0 2255.88  4951.1 2251.78  4961.1 2250.10
  4975.8 2240.99  4979.2 2235.59  4979.4 2235.09  4982.9 2235.09  4983.2 2235.59
  5001.0 2236.44  5005.8 2236.44  5011.2 2235.85  5021.2 2240.32  5031.2 2247.28
  5041.2 2257.78  5046.8 2267.81  5051.8 2268.18  5061.3 2272.63  5081.3 2276.66
  5091.3 2277.31  5111.3 2280.03  5131.4 2282.55  5160.6 2284.37  5164.8 2284.37
#Mann=3,-1,0
  4851.8    0.16       0  4979.2    0.07       0  4983.2    0.16       0
Bank Sta=4979.2,4983.2
Exp/Cntr=0.3,0.1

Type RM Length L Ch R = 1,1282,51,51,51
BEGIN DESCRIPTION:
Elm 57 1282.45
END DESCRIPTION:
XS GIS Cut Line= 3
      1520001.97      6761782.85      1520137.41      6761808.90
      1520300.74      6761799.82
#Sta/Elev= 30
  4865.5 2268.82  4870.0 2267.80  4878.8 2266.17  4888.9 2265.52  4899.1 2264.19
  4916.8 2261.22  4921.9 2259.38  4939.9 2252.31  4950.0 2248.14  4960.2 2244.34
  4968.8 2241.81  4973.9 2238.07  4980.6 2235.86  4988.8 2233.68  4989.0 2233.18
  4992.5 2233.18  4992.8 2233.68  5003.4 2233.93  5021.0 2236.91  5031.1 2242.73
  5041.1 2250.43  5051.1 2260.16  5061.1 2264.74  5081.1 2267.61  5101.2 2272.29
  5108.0 2274.61  5131.2 2277.44  5151.2 2279.22  5161.3 2280.59  5167.0 2280.77
#Mann=3,-1,0
  4865.5    0.16       0  4988.8    0.07       0  4992.8    0.16       0
Bank Sta=4988.8,4992.8
Exp/Cntr=0.3,0.1

Type RM Length L Ch R = 1,1231,39,39,39
BEGIN DESCRIPTION:
Elm 57 1231.12
END DESCRIPTION:
XS GIS Cut Line= 3
      1519992.91      6761807.61      1520106.16      6761850.56
      1520305.40      6761820.61
#Sta/Elev= 30
  4877.9 2266.96  4881.7 2266.96  4894.6 2265.00  4912.2 2263.41  4919.4 2261.86
  4924.8 2261.13  4944.2 2250.47  4949.6 2247.93  4955.0 2241.51  4965.7 2237.00
  4987.1 2233.37  4995.7 2232.69  5006.0 2232.45  5006.2 2231.95  5009.7 2231.95
  5010.0 2232.45  5018.1 2233.01  5038.3 2243.30  5046.6 2249.49  5051.7 2246.76
  5058.5 2254.70  5068.6 2259.27  5078.7 2260.83  5115.7 2265.23  5139.4 2270.93
  5149.5 2273.11  5159.6 2274.71  5179.6 2276.30  5190.0 2278.83  5200.5 2279.05
#Mann=3,-1,0
  4877.9    0.16       0  5006.0    0.07       0  5010.0    0.16       0
Bank Sta=5006,5010
Exp/Cntr=0.3,0.1

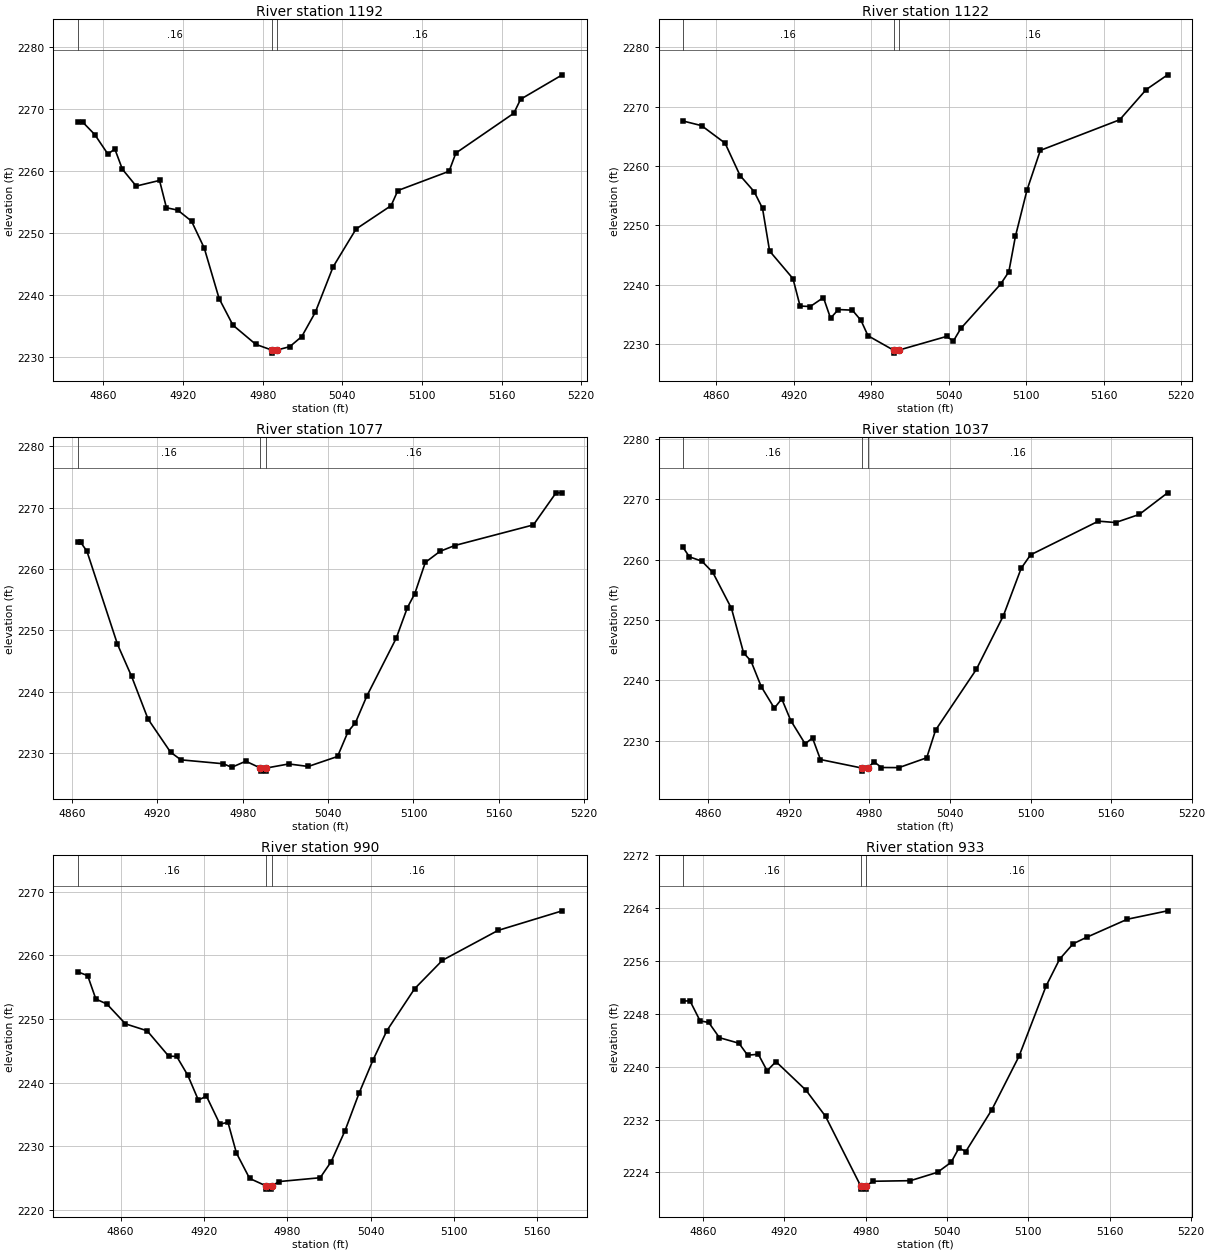
Type RM Length L Ch R = 1,1192,70,70,70
BEGIN DESCRIPTION:
Elm 57 1192
END DESCRIPTION:
XS GIS Cut Line= 3
      1519952.49      6761845.35      1520106.16      6761889.63
      1520306.71      6761845.35
#Sta/Elev= 30
  4840.5 2267.89  4844.4 2267.89  4853.5 2265.87  4863.4 2262.72  4868.6 2263.55
  4874.3 2260.28  4884.7 2257.56  4902.3 2258.47  4907.5 2254.06  4916.0 2253.68
  4926.4 2251.90  4936.0 2247.55  4947.2 2239.40  4957.6 2235.11  4974.8 2232.01
  4986.8 2231.09  4987.1 2230.59  4990.8 2231.09  5000.4 2231.63  5009.5 2233.27
  5019.7 2237.19  5033.1 2244.52  5050.4 2250.63  5076.8 2254.40  5081.9 2256.84
  5120.5 2259.95  5125.6 2262.89  5169.3 2269.32  5174.4 2271.58  5205.8 2275.52
#Mann=3,-1,0
  4840.5    0.16       0  4986.8    0.07       0  4990.8    0.16       0
Bank Sta=4986.8,4990.8
Exp/Cntr=0.3,0.1

Type RM Length L Ch R = 1,1122,45,45,45
BEGIN DESCRIPTION:
Elm 57 1122.45
END DESCRIPTION:
XS GIS Cut Line= 3
      1519934.25      6761888.31      1520086.63      6761953.43
      1520291.17      6762000.03
#Sta/Elev= 30
  4834.1 2267.58  4848.6 2266.79  4866.8 2263.84  4878.4 2258.39  4889.3 2255.68
  4895.8 2252.87  4901.3 2245.67  4919.4 2241.02  4924.9 2236.40  4932.8 2236.32
  4943.0 2237.83  4948.5 2234.35  4954.5 2235.81  4965.4 2235.71  4972.1 2233.98
  4977.5 2231.40  4997.3 2228.97  4997.5 2228.47  5001.3 2228.97  5038.5 2231.29
  5043.6 2230.49  5049.4 2232.62  5080.2 2240.08  5086.6 2242.16  5091.7 2248.13
  5100.7 2255.95  5111.0 2262.62  5172.5 2267.78  5193.0 2272.86  5209.6 2275.35
#Mann=3,-1,0
  4834.1    0.16       0  4997.3    0.07       0  5001.3    0.16       0
Bank Sta=4997.3,5001.3
Exp/Cntr=0.3,0.1

Type RM Length L Ch R = 1,1077,40,40,40
BEGIN DESCRIPTION:
Elm 57 1077.31
END DESCRIPTION:
XS GIS Cut Line= 3
      1519942.14      6761920.90      1520060.59      6761989.89
      1520258.53      6762038.07
#Sta/Elev= 30
  4863.8 2264.40  4865.9 2264.40  4870.4 2262.92  4891.9 2247.73  4901.8 2242.51
  4913.4 2235.53  4929.2 2230.14  4936.5 2228.89  4966.4 2228.25  4972.2 2227.67
  4982.1 2228.67  4992.4 2227.55  4992.7 2227.05  4996.2 2227.05  4996.4 2227.55
  5012.3 2228.22  5026.0 2227.81  5046.6 2229.44  5054.0 2233.49  5059.2 2234.95
  5067.2 2239.30  5087.8 2248.70  5095.7 2253.72  5100.9 2255.99  5108.3 2261.09
  5118.6 2262.89  5128.9 2263.84  5184.3 2267.21  5200.2 2272.44  5204.6 2272.44
#Mann=3,-1,0
  4863.8    0.16       0  4992.4    0.07       0  4996.4    0.16       0
Bank Sta=4992.4,4996.4
Exp/Cntr=0.3,0.1

Type RM Length L Ch R = 1,1037,47,47,47
BEGIN DESCRIPTION:
Elm 57 1036.69
END DESCRIPTION:
XS GIS Cut Line= 3
      1519912.14      6761962.53      1520057.99      6762030.25
      1520255.92      6762058.90
#Sta/Elev= 30
  4841.2 2262.06  4846.1 2260.46  4855.4 2259.74  4863.5 2257.88  4877.4 2251.91
  4886.4 2244.56  4891.9 2243.21  4899.5 2238.99  4909.3 2235.40  4914.8 2236.95
  4921.5 2233.36  4932.2 2229.50  4937.7 2230.47  4943.6 2226.90  4974.7 2225.48
  4974.9 2224.98  4978.7 2225.48  4983.5 2226.53  4989.0 2225.58  5002.0 2225.56
  5022.7 2227.19  5029.3 2231.77  5059.6 2241.81  5079.8 2250.73  5093.0 2258.56
  5100.0 2260.79  5150.5 2266.37  5163.3 2266.14  5180.9 2267.48  5202.0 2271.06
#Mann=3,-1,0
  4841.2    0.16       0  4974.7    0.07       0  4978.7    0.16       0
Bank Sta=4974.7,4978.7
Exp/Cntr=0.3,0.1

Type RM Length L Ch R = 1,990,57,57,57
BEGIN DESCRIPTION:
Elm 57 990.49
END DESCRIPTION:
XS GIS Cut Line= 3
      1519906.95      6761987.29      1520054.08      6762075.82
      1520231.25      6762082.29
#Sta/Elev= 30
  4829.0 2257.44  4836.3 2256.83  4842.2 2253.15  4850.1 2252.38  4863.5 2249.26
  4879.1 2248.17  4894.6 2244.19  4900.4 2244.14  4908.4 2241.17  4916.0 2237.28
  4921.8 2237.91  4931.5 2233.50  4937.3 2233.80  4943.4 2228.97  4952.9 2224.98
  4964.8 2223.80  4965.0 2223.30  4968.5 2223.30  4968.8 2223.80  4974.2 2224.49
  5003.7 2225.09  5011.6 2227.61  5021.6 2232.49  5031.7 2238.37  5041.7 2243.56
  5051.7 2248.18  5071.7 2254.78  5091.7 2259.24  5131.7 2263.93  5178.0 2267.01
#Mann=3,-1,0
  4829.0    0.16       0  4964.8    0.07       0  4968.8    0.16       0
Bank Sta=4964.8,4968.8
Exp/Cntr=0.3,0.1

Type RM Length L Ch R = 1,933,42,42,42
BEGIN DESCRIPTION:
Elm 57 933.46
END DESCRIPTION:
XS GIS Cut Line= 3
      1519901.74      6762023.75      1520021.53      6762121.40
      1520224.68      6762127.91
#Sta/Elev= 30
  4845.0 2249.95  4850.3 2249.95  4857.7 2246.94  4864.1 2246.69  4872.0 2244.39
  4886.4 2243.55  4892.8 2241.74  4900.7 2241.88  4907.2 2239.38  4913.7 2240.77
  4935.9 2236.44  4950.3 2232.49  4976.2 2221.97  4976.5 2221.47  4980.0 2221.47
  4980.2 2221.97  4985.5 2222.66  5013.0 2222.75  5033.0 2224.02  5043.0 2225.53
  5048.8 2227.70  5053.8 2227.15  5073.1 2233.50  5093.1 2241.57  5113.1 2252.21
  5123.1 2256.28  5133.1 2258.61  5143.1 2259.59  5173.1 2262.32  5202.8 2263.59
#Mann=3,-1,0
  4845.0    0.16       0  4976.2    0.07       0  4980.2    0.16       0
Bank Sta=4976.2,4980.2
Exp/Cntr=0.3,0.1

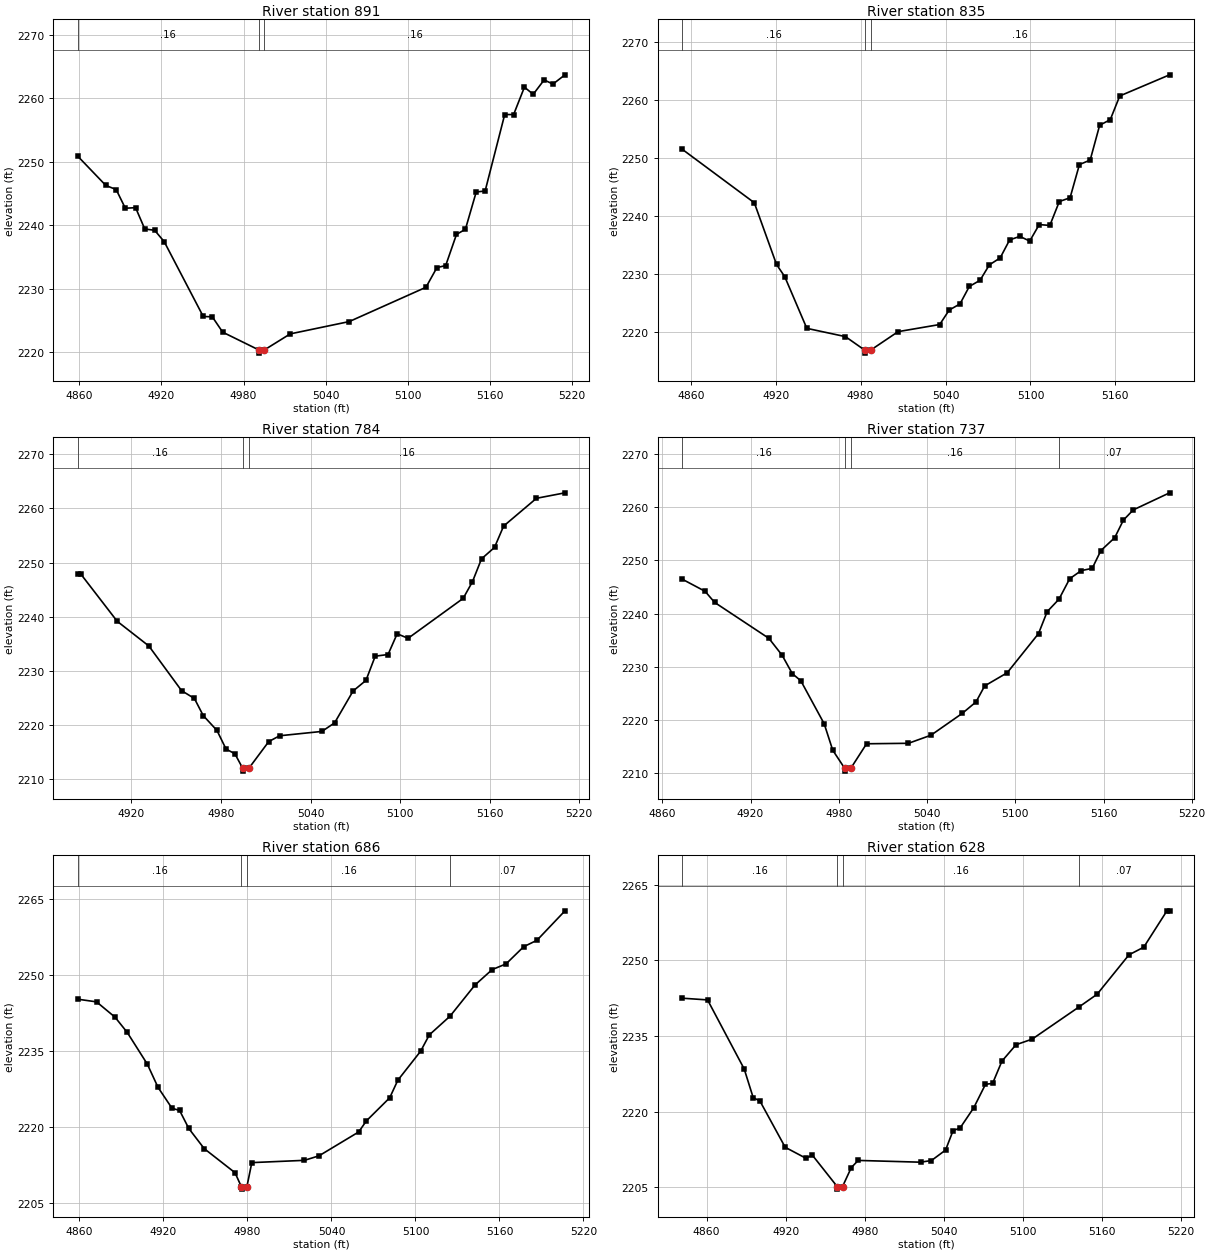
Type RM Length L Ch R = 1,891,56,56,56
BEGIN DESCRIPTION:
Elm 57 890.5
END DESCRIPTION:
XS GIS Cut Line= 3
      1519897.86      6762045.91      1519998.09      6762159.16
      1520126.99      6762318.01
#Sta/Elev= 30
  4858.9 2250.88  4879.5 2246.25  4887.0 2245.62  4893.7 2242.67  4901.2 2242.76
  4907.9 2239.40  4915.1 2239.20  4922.1 2237.40  4950.6 2225.62  4957.2 2225.57
  4964.8 2223.15  4991.2 2220.35  4991.5 2219.85  4995.2 2220.35  5014.1 2222.88
  5057.2 2224.82  5113.2 2230.22  5121.2 2233.32  5127.6 2233.64  5135.5 2238.55
  5142.0 2239.35  5149.9 2245.23  5156.4 2245.38  5170.7 2257.43  5177.2 2257.42
  5185.1 2261.74  5191.5 2260.61  5199.5 2262.88  5205.9 2262.22  5214.7 2263.68
#Mann=3,-1,0
  4858.9    0.16       0  4991.2    0.07       0  4995.2    0.16       0
Bank Sta=4991.2,4995.2
Exp/Cntr=0.3,0.1

Type RM Length L Ch R = 1,835,51,51,51
BEGIN DESCRIPTION:
Elm 57 835.1
END DESCRIPTION:
XS GIS Cut Line= 3
      1519874.38      6762058.88      1519953.82      6762194.31
      1520094.45      6762318.01
#Sta/Elev= 30
  4854.0 2251.54  4904.9 2242.31  4920.6 2231.65  4926.4 2229.55  4942.0 2220.62
  4969.3 2219.19  4983.0 2216.84  4983.2 2216.34  4987.0 2216.84  5006.5 2220.05
  5035.9 2221.28  5042.6 2223.78  5050.2 2224.83  5056.8 2227.85  5064.4 2228.92
  5071.0 2231.59  5078.6 2232.78  5085.3 2235.89  5092.5 2236.50  5099.5 2235.69
  5106.2 2238.54  5113.7 2238.39  5120.4 2242.52  5128.0 2243.17  5134.6 2248.90
  5142.2 2249.68  5148.9 2255.69  5156.4 2256.66  5163.1 2260.75  5198.3 2264.40
#Mann=3,-1,0
  4854.0    0.16       0  4983.0    0.07       0  4987.0    0.16       0
Bank Sta=4983,4987
Exp/Cntr=0.3,0.1

Type RM Length L Ch R = 1,784,47,47,47
BEGIN DESCRIPTION:
Elm 57 784.22
END DESCRIPTION:
XS GIS Cut Line= 3
      1519836.62      6762099.25      1519897.83      6762195.62
      1520070.53      6762318.97
#Sta/Elev= 30
  4884.0 2247.85  4886.2 2247.85  4910.5 2239.16  4931.7 2234.60  4953.6 2226.36
  4962.2 2224.91  4968.1 2221.76  4977.3 2219.01  4983.4 2215.57  4989.3 2214.71
  4994.6 2212.00  4994.9 2211.50  4998.6 2212.00  5012.0 2216.96  5019.3 2218.03
  5047.6 2218.83  5056.1 2220.41  5068.5 2226.30  5077.1 2228.25  5083.3 2232.72
  5091.9 2233.03  5098.0 2236.86  5105.3 2236.02  5142.2 2243.39  5148.4 2246.45
  5154.5 2250.69  5163.2 2252.80  5169.3 2256.74  5191.3 2261.87  5210.4 2262.88
#Mann=3,-1,0
  4884.0    0.16       0  4994.6    0.07       0  4998.6    0.16       0
Bank Sta=4994.6,4998.6
Exp/Cntr=0.3,0.1

Type RM Length L Ch R = 1,737,51,51,51
BEGIN DESCRIPTION:
Elm 57 736.68
END DESCRIPTION:
XS GIS Cut Line= 3
      1519802.77      6762118.78      1519867.88      6762234.68
      1520035.88      6762340.16
#Sta/Elev= 30
  4873.6 2246.47  4889.1 2244.20  4895.6 2242.11  4932.5 2235.36  4941.5 2232.18
  4948.4 2228.73  4954.2 2227.39  4970.1 2219.30  4975.9 2214.34  4984.1 2210.91
  4984.3 2210.41  4988.1 2210.91  4998.9 2215.55  5027.4 2215.64  5042.7 2217.16
  5063.9 2221.25  5073.3 2223.41  5079.2 2226.42  5094.5 2228.89  5115.8 2236.25
  5121.7 2240.38  5129.7 2242.71  5137.0 2246.56  5144.8 2248.08  5152.3 2248.51
  5158.2 2251.85  5167.6 2254.27  5173.5 2257.57  5180.2 2259.49  5204.9 2262.70
#Mann=4,-1,0
  4873.6    0.16       0  4984.1    0.07       0  4988.1    0.16       0
  5129.7    0.07       0
Bank Sta=4984.1,4988.1
Exp/Cntr=0.3,0.1

Type RM Length L Ch R = 1,686,58,58,58
BEGIN DESCRIPTION:
Elm 57 686.31
END DESCRIPTION:
XS GIS Cut Line= 3
      1519770.24      6762135.75      1519830.12      6762267.23
      1520011.21      6762360.36
#Sta/Elev= 30
  4858.7 2245.17  4872.2 2244.64  4885.4 2241.62  4894.1 2238.62  4908.5 2232.34
  4916.1 2227.78  4926.1 2223.65  4931.5 2223.23  4938.1 2219.66  4949.1 2215.69
  4971.1 2210.94  4975.6 2208.20  4975.9 2207.70  4979.6 2208.20  4983.1 2212.93
  5020.7 2213.38  5031.1 2214.27  5059.4 2218.97  5065.0 2221.18  5081.6 2225.72
  5087.4 2229.18  5103.7 2234.91  5109.9 2238.13  5124.7 2241.82  5142.5 2247.96
  5154.8 2251.01  5164.7 2252.13  5177.3 2255.52  5186.8 2256.79  5206.8 2262.60
#Mann=4,-1,0
  4858.7    0.16       0  4975.6    0.07       0  4979.6    0.16       0
  5124.7    0.07       0
Bank Sta=4975.6,4979.6
Exp/Cntr=0.3,0.1

Type RM Length L Ch R = 1,628,39,39,39
BEGIN DESCRIPTION:
Elm 57 627.55
END DESCRIPTION:
XS GIS Cut Line= 3
      1519745.48      6762152.62      1519787.15      6762306.29
      1519983.72      6762381.80
#Sta/Elev= 30
  4841.5 2242.52  4860.7 2242.18  4888.5 2228.49  4895.3 2222.83  4900.5 2222.11
  4919.6 2212.97  4935.2 2210.81  4940.3 2211.38  4959.1 2205.17  4959.3 2204.67
  4963.1 2205.17  4969.8 2208.95  4975.0 2210.36  5022.3 2210.01  5030.6 2210.34
  5041.3 2212.41  5047.0 2216.27  5052.3 2216.78  5062.7 2220.80  5071.6 2225.45
  5077.0 2225.63  5084.1 2230.05  5094.8 2233.30  5107.0 2234.40  5142.6 2240.79
  5156.3 2243.30  5180.5 2251.12  5191.7 2252.63  5209.3 2259.84  5211.3 2259.84
#Mann=4,-1,0
  4841.5    0.16       0  4959.1    0.07       0  4963.1    0.16       0
  5142.6    0.07       0
Bank Sta=4959.1,4963.1
Exp/Cntr=0.3,0.1