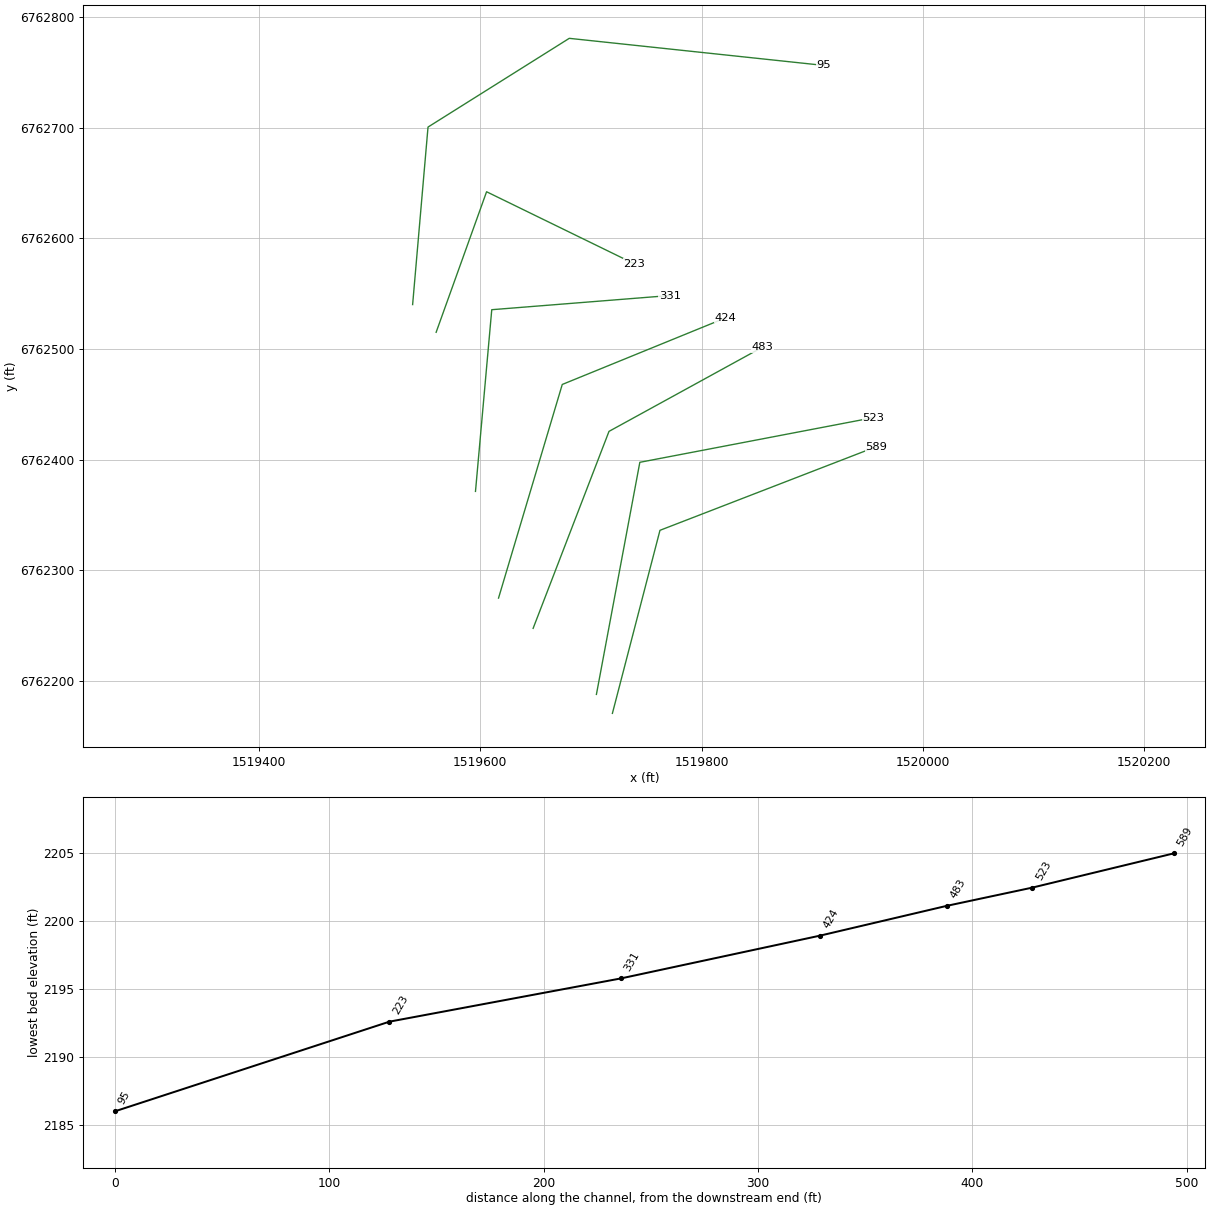
HEC-RAS study Elm 57.prj: Elm 57 Base Level Engineering

--- Elm 57.g01 (geometry) --- (continued)

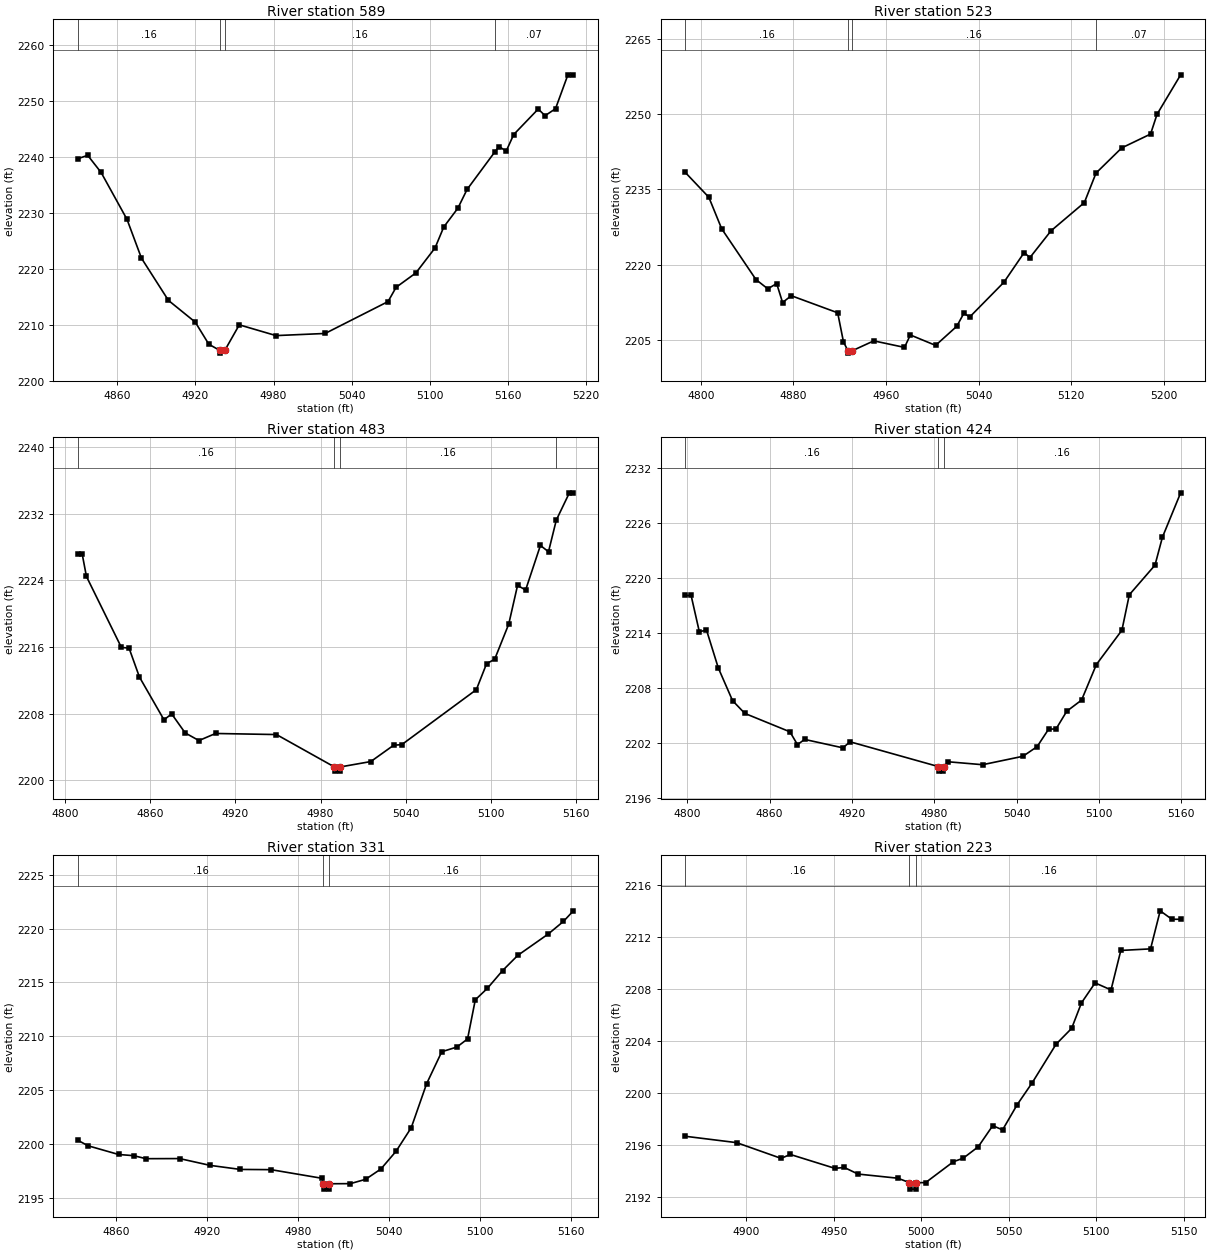
Type RM Length L Ch R = 1,589,66,66,66
BEGIN DESCRIPTION:
Elm 57 588.68
END DESCRIPTION:
XS GIS Cut Line= 3
      1519719.44      6762170.87      1519762.41      6762336.24
      1519957.76      6762411.77
#Sta/Elev= 30
  4829.9 2239.67  4837.3 2240.26  4847.6 2237.20  4867.5 2228.82  4878.6 2221.89
  4899.3 2214.36  4919.9 2210.48  4930.3 2206.54  4938.6 2205.45  4938.8 2204.95
  4942.6 2205.45  4953.7 2210.00  4981.9 2208.08  5019.6 2208.46  5067.9 2214.15
  5074.1 2216.70  5089.3 2219.27  5104.0 2223.73  5110.7 2227.47  5121.5 2230.81
  5128.6 2234.17  5150.1 2240.93  5153.2 2241.83  5158.6 2241.00  5164.4 2243.97
  5183.2 2248.52  5188.5 2247.34  5196.5 2248.58  5206.0 2254.63  5210.2 2254.63
#Mann=4,-1,0
  4829.9    0.16       0  4938.6    0.07       0  4942.6    0.16       0
  5150.1    0.07       0
Bank Sta=4938.6,4942.6
Exp/Cntr=0.3,0.1

Type RM Length L Ch R = 1,523,40,40,40
BEGIN DESCRIPTION:
Elm 57 522.861
END DESCRIPTION:
XS GIS Cut Line= 3
      1519705.00      6762188.01      1519744.22      6762397.68
      1519955.00      6762438.00
#Sta/Elev= 30
  4786.7 2238.36  4807.0 2233.43  4818.1 2227.16  4847.7 2217.07  4857.9 2215.23
  4865.6 2216.27  4870.7 2212.50  4878.2 2213.86  4918.3 2210.46  4923.3 2204.68
  4927.1 2202.94  4927.4 2202.44  4931.1 2202.94  4949.5 2204.88  4976.0 2203.58
  4981.1 2206.05  5002.9 2203.98  5021.2 2207.78  5027.3 2210.36  5032.4 2209.63
  5061.9 2216.53  5079.4 2222.43  5084.4 2221.44  5102.6 2226.76  5131.4 2232.37
  5141.5 2238.25  5163.7 2243.25  5188.6 2246.00  5194.2 2249.93  5214.6 2257.78
#Mann=4,-1,0
  4786.7    0.16       0  4927.1    0.07       0  4931.1    0.16       0
  5141.5    0.07       0
Bank Sta=4927.1,4931.1
Exp/Cntr=0.3,0.1

Type RM Length L Ch R = 1,483,59,59,59
BEGIN DESCRIPTION:
Elm 57 4781
END DESCRIPTION:
XS GIS Cut Line= 3
      1519647.82      6762247.68      1519716.37      6762425.63
      1519854.89      6762501.62
#Sta/Elev= 30
  4809.3 2227.17  4812.2 2227.17  4815.2 2224.47  4839.8 2215.95  4845.2 2215.87
  4852.5 2212.40  4869.8 2207.26  4875.2 2207.97  4884.7 2205.69  4894.4 2204.77
  4906.1 2205.62  4949.0 2205.49  4989.8 2201.60  4990.1 2201.10  4993.6 2201.10
  4993.8 2201.60  5015.4 2202.25  5031.5 2204.21  5037.2 2204.28  5089.7 2210.88
  5096.9 2214.00  5102.6 2214.53  5112.5 2218.75  5118.7 2223.39  5124.4 2222.85
  5134.8 2228.19  5140.5 2227.44  5146.0 2231.24  5155.2 2234.51  5158.0 2234.51
#Mann=4,-1,0
  4809.3    0.16       0  4989.8    0.07       0  4993.8    0.16       0
  5146.0    0.07       0
Bank Sta=4989.8,4993.8
Exp/Cntr=0.3,0.1

Type RM Length L Ch R = 1,424,93,93,93
BEGIN DESCRIPTION:
Elm 57 4780
END DESCRIPTION:
XS GIS Cut Line= 3
      1519616.57      6762275.02      1519674.14      6762468.01
      1519821.84      6762528.23
#Sta/Elev= 30
  4798.6 2218.08  4802.8 2218.08  4808.8 2214.12  4814.0 2214.32  4822.6 2210.18
  4833.0 2206.61  4841.9 2205.22  4874.8 2203.21  4880.3 2201.81  4885.5 2202.38
  4913.4 2201.46  4918.6 2202.12  4982.9 2199.42  4983.2 2198.92  4986.7 2198.92
  4986.9 2199.42  4990.1 2199.94  5015.2 2199.62  5044.6 2200.54  5054.9 2201.59
  5063.3 2203.50  5068.7 2203.52  5076.5 2205.45  5087.3 2206.67  5098.1 2210.55
  5116.7 2214.29  5122.1 2218.16  5140.8 2221.39  5146.2 2224.43  5159.5 2229.28
#Mann=3,-1,0
  4798.6    0.16       0  4982.9    0.07       0  4986.9    0.16       0
Bank Sta=4982.9,4986.9
Exp/Cntr=0.3,0.1

Type RM Length L Ch R = 1,331,108,108,108
BEGIN DESCRIPTION:
Elm 57 4779
END DESCRIPTION:
XS GIS Cut Line= 3
      1519595.75      6762371.41      1519610.45      6762535.55
      1519771.44      6762548.37
#Sta/Elev= 30
  4835.2 2200.31  4841.8 2199.81  4861.9 2199.00  4871.9 2198.89  4879.9 2198.61
  4902.1 2198.62  4922.1 2197.99  4942.2 2197.61  4962.3 2197.59  4996.2 2196.78
  4996.7 2196.28  4997.0 2195.78  5000.5 2195.78  5000.7 2196.28  5014.6 2196.29
  5024.6 2196.69  5034.7 2197.65  5044.7 2199.30  5054.7 2201.49  5064.8 2205.57
  5074.8 2208.55  5084.8 2208.99  5091.8 2209.74  5096.9 2213.38  5104.9 2214.45
  5114.9 2216.10  5124.9 2217.51  5145.0 2219.50  5155.0 2220.67  5161.5 2221.65
#Mann=3,-1,0
  4835.2    0.16       0  4996.7    0.07       0  5000.7    0.16       0
Bank Sta=4996.7,5000.7
Exp/Cntr=0.3,0.1

Type RM Length L Ch R = 1,223,128,128,128
BEGIN DESCRIPTION:
Elm 57 4778
END DESCRIPTION:
XS GIS Cut Line= 3
      1519560.20      6762515.14      1519605.77      6762642.11
      1519738.97      6762577.13
#Sta/Elev= 30
  4865.1 2196.68  4894.4 2196.19  4919.8 2194.98  4925.1 2195.28  4950.6 2194.21
  4955.9 2194.28  4963.8 2193.77  4986.6 2193.45  4993.2 2193.11  4993.4 2192.61
  4996.9 2192.61  4997.2 2193.11  5002.4 2193.11  5018.3 2194.72  5023.9 2194.99
  5032.5 2195.87  5040.8 2197.50  5046.4 2197.17  5054.8 2199.12  5063.4 2200.81
  5077.0 2203.77  5085.9 2204.99  5091.5 2206.95  5099.3 2208.49  5108.4 2207.95
  5114.0 2210.99  5131.0 2211.11  5136.5 2214.04  5143.2 2213.39  5148.2 2213.39
#Mann=3,-1,0
  4865.1    0.16       0  4993.2    0.07       0  4997.2    0.16       0
Bank Sta=4993.2,4997.2
Exp/Cntr=0.3,0.1

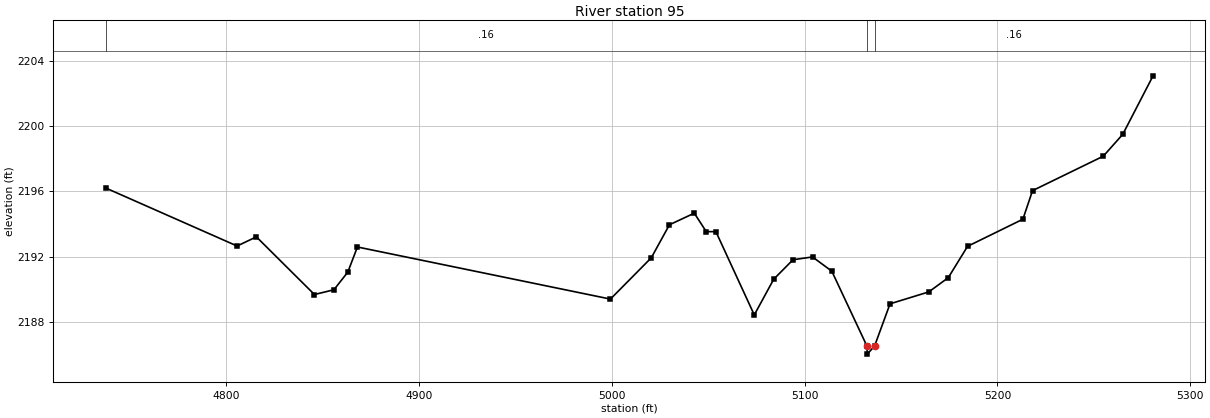
Type RM Length L Ch R = 1,95,0,0,0
BEGIN DESCRIPTION:
aaaaa1
END DESCRIPTION:
XS GIS Cut Line= 4
      1519538.96      6762540.18      1519552.87      6762700.54
      1519680.48      6762780.70      1519910.62      6762756.22
#Sta/Elev= 30
  4737.6 2196.21  4805.7 2192.66  4815.7 2193.22  4845.8 2189.69  4855.9 2189.98
  4863.1 2191.06  4868.1 2192.60  4999.3 2189.41  5020.5 2191.94  5029.9 2193.96
  5042.8 2194.67  5049.0 2193.54  5054.0 2193.54  5073.9 2188.44  5084.0 2190.63
  5094.0 2191.82  5104.1 2191.99  5114.1 2191.12  5132.3 2186.54  5132.5 2186.04
  5136.3 2186.54  5144.3 2189.12  5164.4 2189.85  5174.5 2190.72  5184.5 2192.64
  5213.2 2194.30  5218.2 2196.05  5254.9 2198.16  5265.0 2199.50  5280.7 2203.08
#Mann=3,-1,0
  4737.6    0.16       0  5132.3    0.07       0  5136.3    0.16       0
Bank Sta=5132.3,5136.3
Exp/Cntr=0.3,0.1

Chan Stop Cuts=-1