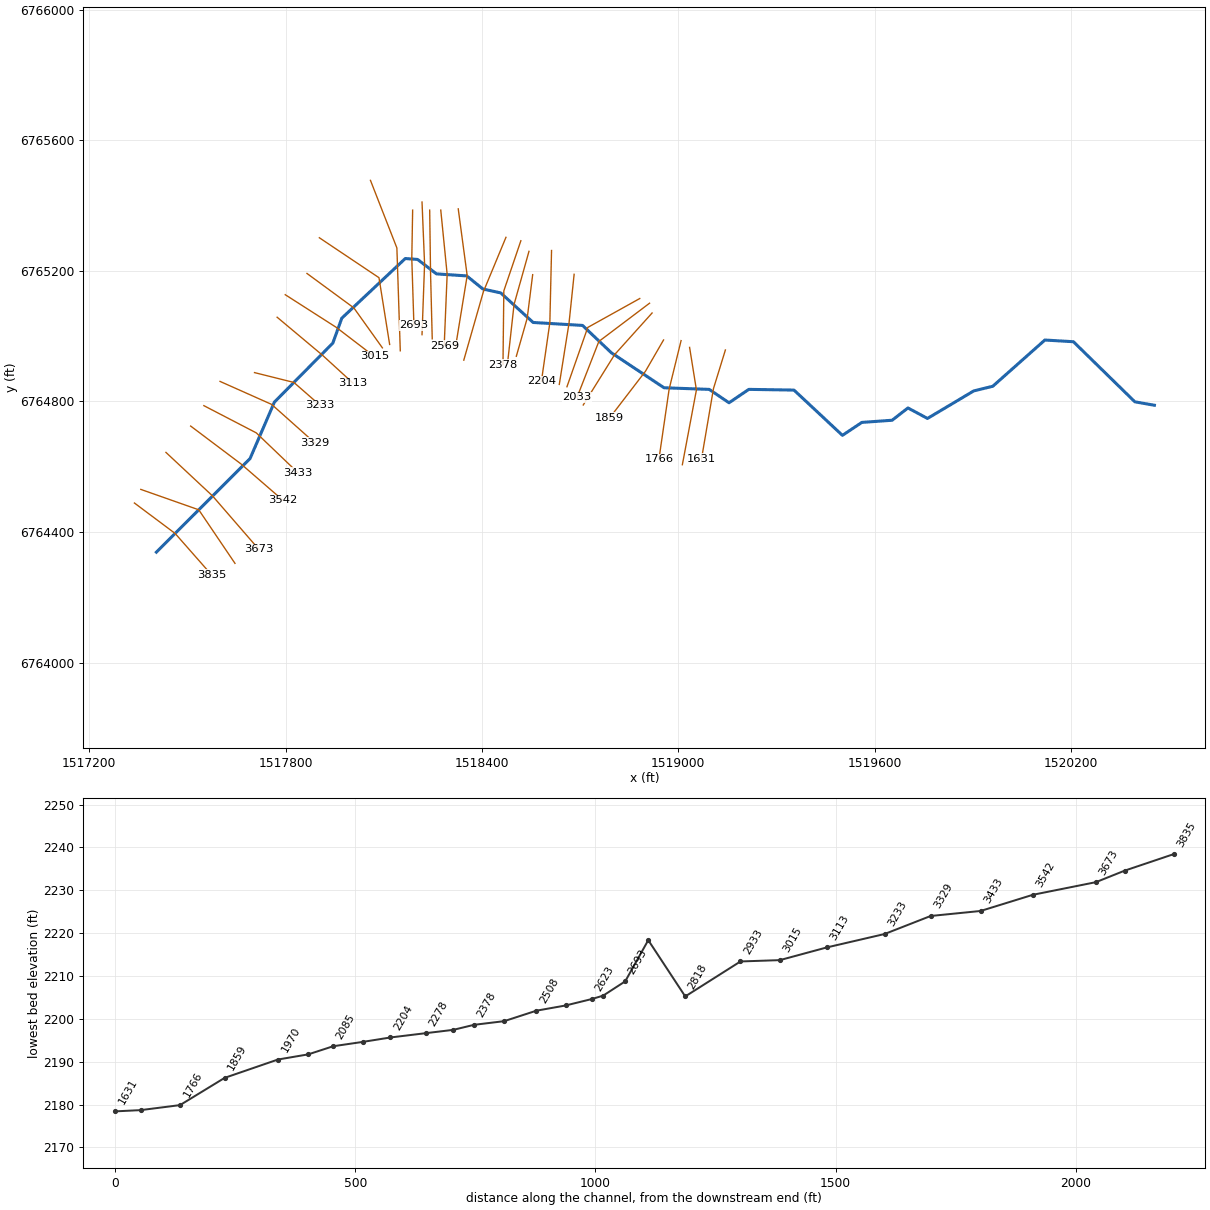
--- Elm 58.prj (project) ---

Proj Title=Elm 58 Base Level Engineering
Current Plan=p01
Default Exp/Contr=0.3,0.1
English Units
Geom File=g01
Flow File=f01
Plan File=p01
BEGIN DESCRIPTION:
Elm 58
END DESCRIPTION:

--- Elm 58.p01 (plan) ---

Plan Title=Multiple Run
Short Identifier=Multiple
Geom File=g01
Flow File=f01
Subcritical Flow
K Sum by GR= 0
Std Step Tol= 0.01
Critical Tol= 0.01
Num of Std Step Trials= 20
Max Error Tol= 0.3
Flow Tol Ratio= 0.001
Split Flow NTrial= 30
Split Flow Tol= 0.02
Split Flow Ratio= 0.02
Log Output Level= 0
Friction Slope Method= 1
Unsteady Friction Slope Method= 2
Unsteady Bridges Friction Slope Method= 1
Parabolic Critical Depth
Global Vel Dist=  1 , 1 , 1
Global Log Level= 0
CheckData=True
Encroach Param= -1, 0, 0, 0
BEGIN DESCRIPTION:
Multiple Run
END DESCRIPTION:

--- Elm 58.f01 (steady flow) ---

Flow Title=Multiple
Number of Profiles=7
Profile Names=10-year,25-year,50-year,1pct_min,100-year,1pct_plu,500-year
River Rch & RM= Elm 58,Reach-1,3835
     198     277     342     264     423     582     653
Boundary for River Rch & Prof#=Elm 58,Reach-1,1
Up Type=0
Dn Type=3
Dn Slope=0.005
Boundary for River Rch & Prof#=Elm 58,Reach-1,2
Up Type=0
Dn Type=3
Dn Slope=0.005
Boundary for River Rch & Prof#=Elm 58,Reach-1,3
Up Type=0
Dn Type=3
Dn Slope=0.005
Boundary for River Rch & Prof#=Elm 58,Reach-1,4
Up Type=0
Dn Type=3
Dn Slope=0.005
Boundary for River Rch & Prof#=Elm 58,Reach-1,5
Up Type=0
Dn Type=3
Dn Slope=0.005
Boundary for River Rch & Prof#=Elm 58,Reach-1,6
Up Type=0
Dn Type=3
Dn Slope=0.005
Boundary for River Rch & Prof#=Elm 58,Reach-1,7
Up Type=0
Dn Type=3
Dn Slope=0.005

--- Elm 58.g01 (geometry) ---

Geom Title=Existing Conditions

River Reach=Elm 58,Reach-1
Reach XY= 30
      1517405.00      6764338.00      1517691.38      6764624.79
      1517765.76      6764797.68      1517944.22      6764978.32
      1517971.65      6765054.67      1518165.62      6765237.40
      1518203.25      6765234.66      1518260.97      6765190.38
      1518353.42      6765184.18      1518402.83      6765144.14
      1518457.29      6765132.15      1518556.47      6765041.55
      1518707.44      6765032.52      1518795.33      6764948.80
      1518956.47      6764841.55      1519094.56      6764836.60
      1519155.00      6764795.56      1519215.44      6764836.63
      1519353.53      6764834.47      1519501.58      6764695.79
      1519560.89      6764735.44      1519653.50      6764742.08
      1519701.78      6764779.72      1519761.55      6764747.58
      1519902.81      6764831.89      1519961.06      6764846.14
      1520120.22      6764987.76      1520207.43      6764982.60
      1520395.21      6764798.52      1520455.00      6764788.00

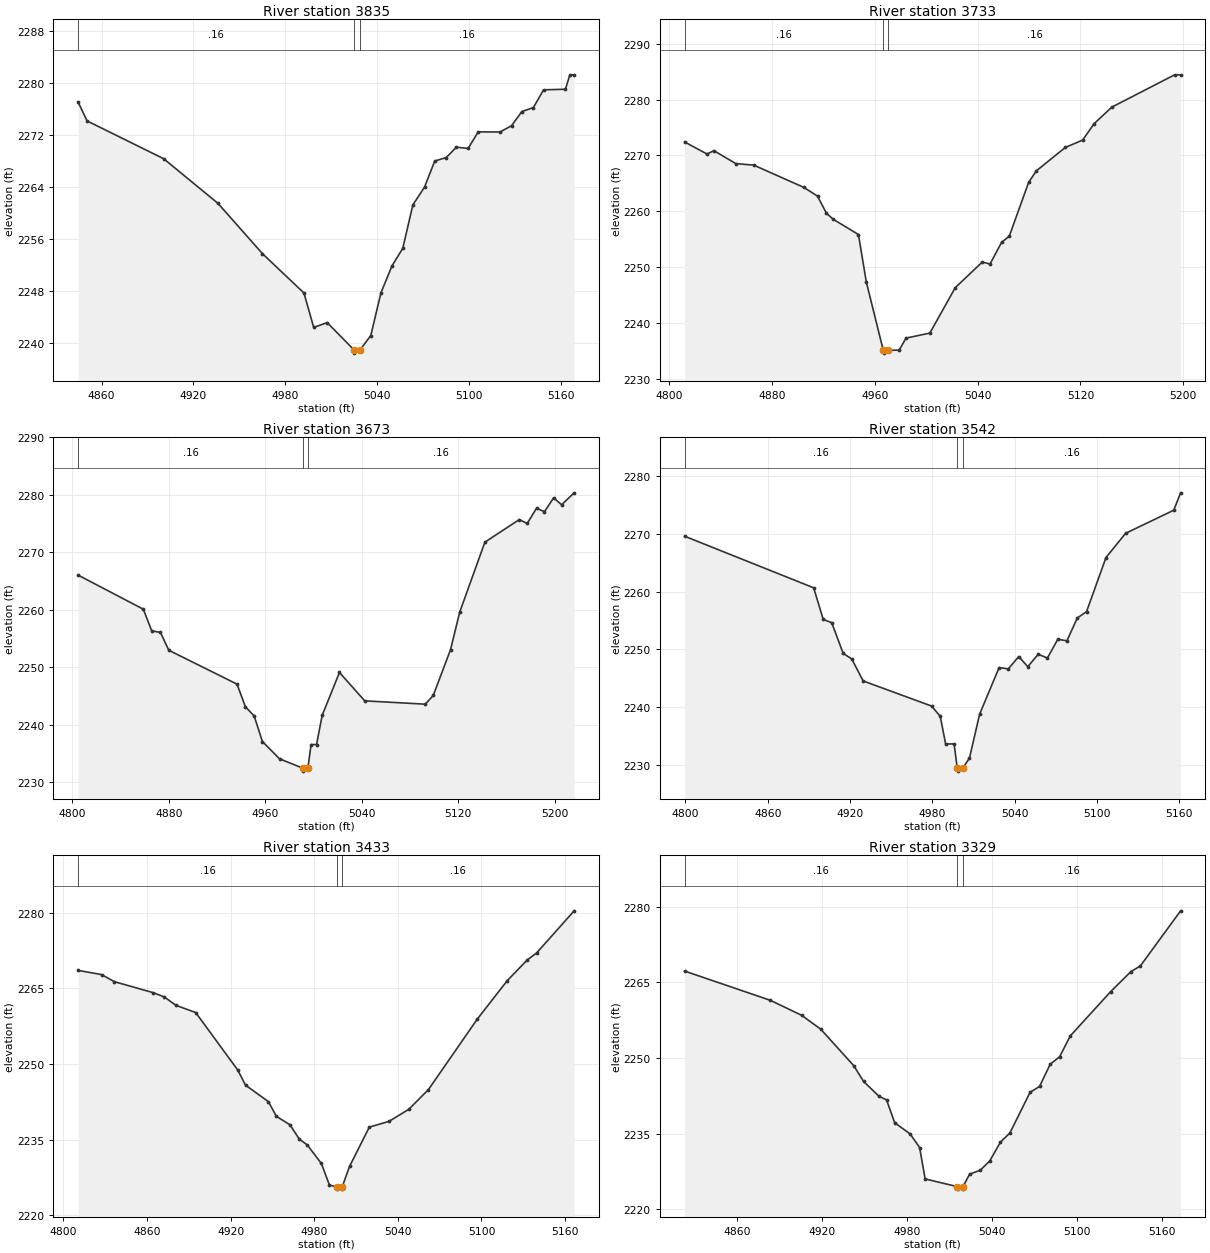
Type RM Length L Ch R = 1,3835,102,102,102
BEGIN DESCRIPTION:
Elm 58 4852
END DESCRIPTION:
XS GIS Cut Line= 3
      1517337.94      6764488.58      1517462.28      6764395.36
      1517573.64      6764268.50
#Sta/Elev= 30
  4844.6 2277.07  4850.5 2274.16  4900.5 2268.35  4936.0 2261.48  4965.1 2253.73
  4992.2 2247.68  4998.6 2242.37  5007.4 2243.12  5024.9 2238.92  5025.1 2238.42
  5028.9 2238.92  5035.9 2241.13  5042.5 2247.67  5049.7 2251.83  5056.8 2254.55
  5063.4 2261.24  5071.0 2263.97  5077.7 2267.99  5085.2 2268.53  5091.9 2270.13
  5099.5 2269.92  5106.1 2272.48  5120.4 2272.46  5127.9 2273.43  5134.6 2275.60
  5142.2 2276.23  5148.8 2278.95  5163.1 2279.04  5166.0 2281.26  5168.8 2281.26
#Mann=3,-1,0
  4844.6    0.16       0  5024.9    0.07       0  5028.9    0.16       0
Bank Sta=5024.9,5028.9
Exp/Cntr=0.3,0.1

Type RM Length L Ch R = 1,3733,60,60,60
BEGIN DESCRIPTION:
Elm 58 4853
END DESCRIPTION:
XS GIS Cut Line= 3
      1517357.47      6764530.25      1517534.56      6764467.74
      1517645.23      6764303.68
#Sta/Elev= 30
  4812.2 2272.41  4829.7 2270.24  4835.0 2270.85  4852.0 2268.53  4866.0 2268.25
  4905.0 2264.26  4915.6 2262.69  4922.5 2259.64  4927.8 2258.55  4947.4 2255.82
  4953.5 2247.34  4966.7 2235.07  4966.9 2234.57  4970.7 2235.07  4979.1 2235.11
  4984.4 2237.26  5002.9 2238.16  5022.7 2246.30  5043.7 2250.89  5049.7 2250.54
  5058.7 2254.41  5064.7 2255.53  5079.7 2265.14  5085.7 2267.22  5108.3 2271.43
  5121.7 2272.73  5130.6 2275.67  5144.4 2278.64  5193.2 2284.43  5197.9 2284.43
#Mann=3,-1,0
  4812.2    0.16       0  4966.7    0.07       0  4970.7    0.16       0
Bank Sta=4966.7,4970.7
Exp/Cntr=0.3,0.1

Type RM Length L Ch R = 1,3673,131,131,131
BEGIN DESCRIPTION:
Elm 58 3673.141
END DESCRIPTION:
XS GIS Cut Line= 3
      1517434.27      6764643.56      1517576.83      6764510.07
      1517718.12      6764346.69
#Sta/Elev= 30
  4804.7 2266.02  4858.8 2260.08  4865.7 2256.33  4873.0 2256.03  4879.9 2252.93
  4936.5 2247.03  4943.4 2243.10  4950.7 2241.48  4957.5 2237.04  4971.7 2234.03
  4991.2 2232.38  4991.4 2231.88  4995.2 2232.38  4997.9 2236.51  5002.4 2236.51
  5007.1 2241.60  5021.4 2249.06  5042.4 2244.12  5092.6 2243.54  5099.2 2245.07
  5113.5 2253.03  5121.1 2259.56  5142.0 2271.76  5170.5 2275.69  5177.1 2275.02
  5184.8 2277.66  5191.4 2277.06  5199.0 2279.48  5205.6 2278.27  5216.0 2280.35
#Mann=3,-1,0
  4804.7    0.16       0  4991.2    0.07       0  4995.2    0.16       0
Bank Sta=4991.2,4995.2
Exp/Cntr=0.3,0.1

Type RM Length L Ch R = 1,3542,109,109,109
BEGIN DESCRIPTION:
Elm 58 3541.8
END DESCRIPTION:
XS GIS Cut Line= 3
      1517509.84      6764724.24      1517663.46      6764608.38
      1517791.18      6764497.42
#Sta/Elev= 30
  4799.4 2269.61  4893.5 2260.68  4900.5 2255.20  4906.7 2254.63  4915.0 2249.33
  4921.3 2248.35  4929.6 2244.55  4979.5 2240.20  4985.8 2238.42  4989.7 2233.65
  4995.9 2233.65  4998.2 2229.44  4998.5 2228.94  5002.2 2229.44  5007.1 2231.21
  5014.5 2238.81  5028.7 2246.87  5035.4 2246.64  5043.0 2248.78  5049.6 2247.02
  5057.2 2249.17  5063.9 2248.52  5071.5 2251.77  5078.1 2251.50  5085.7 2255.45
  5092.4 2256.54  5106.6 2265.92  5120.9 2270.11  5156.0 2274.11  5161.0 2277.12
#Mann=3,-1,0
  4799.4    0.16       0  4998.2    0.07       0  5002.2    0.16       0
Bank Sta=4998.2,5002.2
Exp/Cntr=0.3,0.1

Type RM Length L Ch R = 1,3433,104,104,104
BEGIN DESCRIPTION:
Elm 58 3432.79
END DESCRIPTION:
XS GIS Cut Line= 3
      1517550.14      6764786.78      1517710.33      6764703.43
      1517836.93      6764582.00
#Sta/Elev= 30
  4810.5 2268.56  4827.3 2267.73  4836.6 2266.32  4864.4 2264.14  4872.3 2263.30
  4880.8 2261.62  4894.9 2260.20  4925.0 2248.82  4930.7 2245.78  4947.1 2242.52
  4952.8 2239.60  4962.5 2237.94  4969.3 2235.06  4974.9 2233.95  4985.1 2230.25
  4990.9 2225.94  4996.1 2225.66  4996.3 2225.16  4999.8 2225.16  5000.1 2225.66
  5005.3 2229.66  5019.5 2237.46  5033.6 2238.60  5047.8 2240.99  5061.9 2244.90
  5097.1 2258.94  5118.5 2266.53  5132.7 2270.60  5139.6 2272.03  5166.5 2280.38
#Mann=3,-1,0
  4810.5    0.16       0  4996.1    0.07       0  5000.1    0.16       0
Bank Sta=4996.1,5000.1
Exp/Cntr=0.3,0.1

Type RM Length L Ch R = 1,3329,96,96,96
BEGIN DESCRIPTION:
Elm 58 3329.1
END DESCRIPTION:
XS GIS Cut Line= 3
      1517599.63      6764860.99      1517757.21      6764790.67
      1517889.47      6764672.53
#Sta/Elev= 30
  4823.0 2267.27  4883.6 2261.45  4905.5 2258.50  4919.1 2255.72  4942.3 2248.50
  4949.3 2245.35  4960.1 2242.43  4965.5 2241.69  4971.2 2237.18  4982.2 2234.92
  4988.8 2232.24  4992.7 2226.01  5015.4 2224.49  5015.6 2223.99  5019.1 2223.99
  5019.4 2224.49  5024.1 2226.97  5031.6 2227.74  5038.3 2229.60  5045.8 2233.31
  5052.5 2235.14  5066.7 2243.20  5073.4 2244.37  5080.9 2248.77  5087.6 2250.27
  5095.1 2254.41  5123.6 2263.20  5137.8 2267.15  5144.5 2268.28  5172.9 2279.22
#Mann=3,-1,0
  4823.0    0.16       0  5015.4    0.07       0  5019.4    0.16       0
Bank Sta=5015.4,5019.4
Exp/Cntr=0.3,0.1

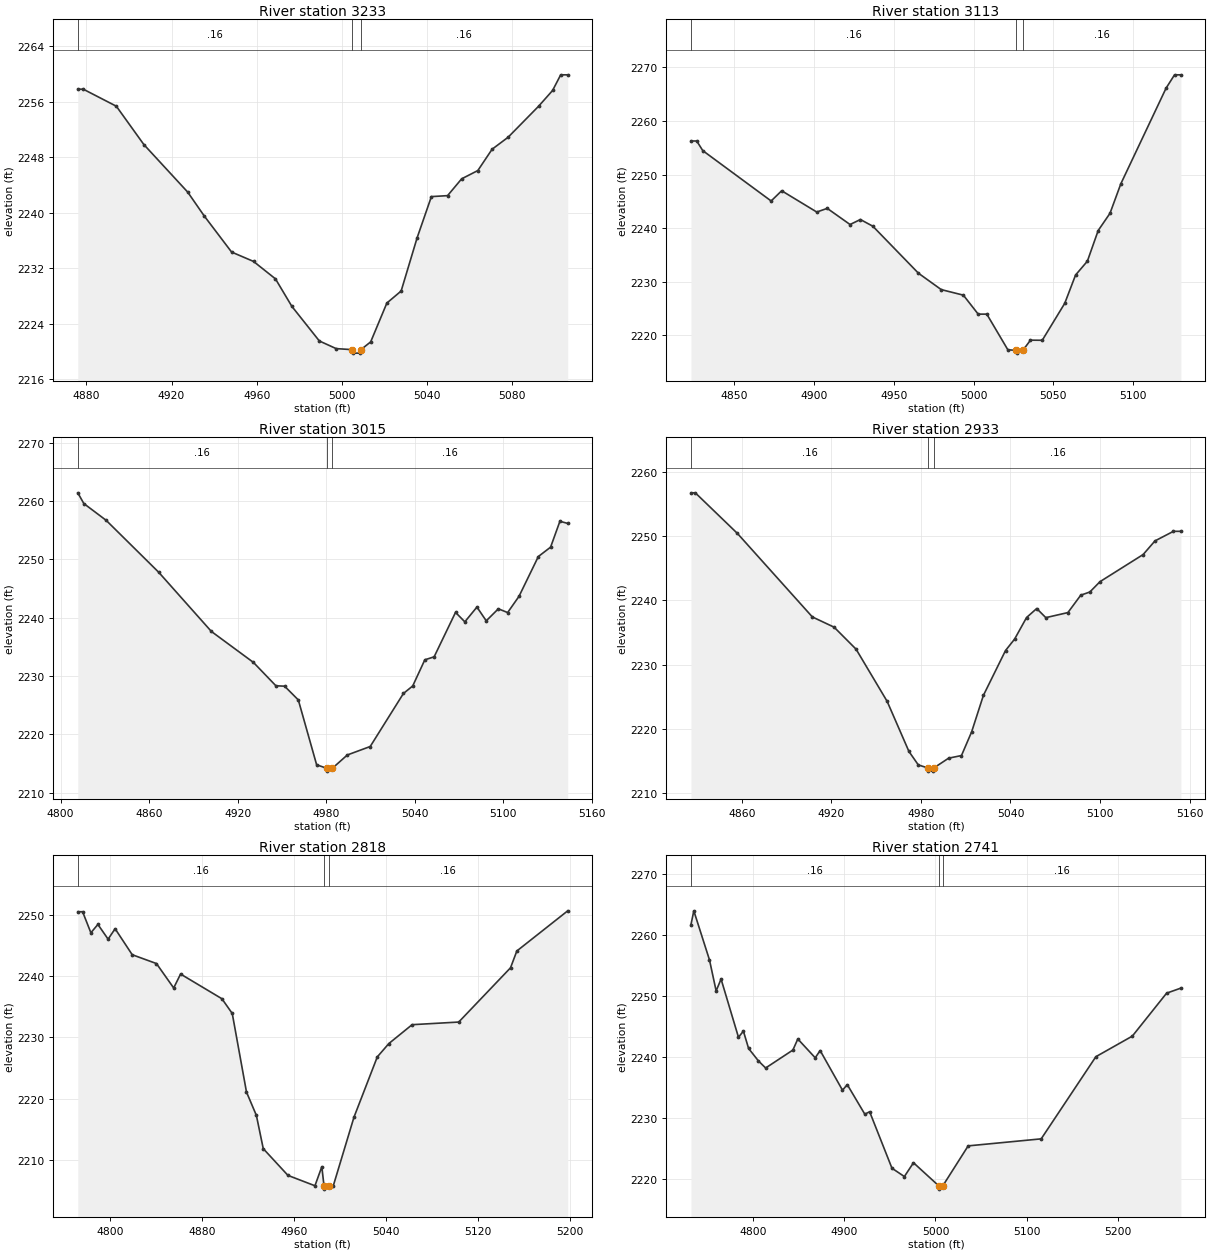
Type RM Length L Ch R = 1,3233,120,120,120
BEGIN DESCRIPTION:
Elm 58 3233.195
END DESCRIPTION:
XS GIS Cut Line= 3
      1517704.96      6764888.01      1517825.25      6764857.90
      1517904.97      6764788.03
#Sta/Elev= 30
  4876.0 2257.77  4878.6 2257.77  4894.1 2255.32  4907.0 2249.81  4927.6 2242.96
  4935.3 2239.55  4948.2 2234.33  4958.5 2232.98  4968.8 2230.47  4976.5 2226.51
  4989.4 2221.53  4997.3 2220.43  5004.9 2220.28  5005.1 2219.78  5008.6 2219.78
  5008.9 2220.28  5013.5 2221.40  5021.1 2226.99  5027.8 2228.72  5035.3 2236.38
  5042.0 2242.31  5049.6 2242.45  5056.2 2244.87  5063.8 2246.06  5070.5 2249.13
  5078.0 2250.85  5092.3 2255.31  5098.9 2257.59  5102.7 2259.84  5106.0 2259.84
#Mann=3,-1,0
  4876.0    0.16       0  5004.9    0.07       0  5008.9    0.16       0
Bank Sta=5004.9,5008.9
Exp/Cntr=0.3,0.1

Type RM Length L Ch R = 1,3113,98,98,98
BEGIN DESCRIPTION:
Elm 58 3112.73
END DESCRIPTION:
XS GIS Cut Line= 3
      1517774.13      6765057.60      1517912.15      6764941.71
      1518005.90      6764855.78
#Sta/Elev= 30
  4822.7 2256.26  4826.3 2256.26  4830.1 2254.46  4873.0 2245.06  4879.6 2246.97
  4901.6 2243.00  4908.2 2243.68  4922.5 2240.67  4929.0 2241.60  4936.8 2240.35
  4965.4 2231.58  4979.7 2228.52  4993.6 2227.48  5002.9 2223.94  5008.3 2223.94
  5021.5 2217.29  5026.9 2217.16  5027.1 2216.66  5030.9 2217.16  5035.7 2219.08
  5043.1 2219.06  5057.2 2225.95  5064.0 2231.24  5071.4 2233.82  5078.2 2239.55
  5085.6 2242.76  5092.4 2248.27  5120.8 2266.13  5126.1 2268.61  5130.1 2268.61
#Mann=3,-1,0
  4822.7    0.16       0  5026.9    0.07       0  5030.9    0.16       0
Bank Sta=5026.9,5030.9
Exp/Cntr=0.3,0.1

Type RM Length L Ch R = 1,3015,82,82,82
BEGIN DESCRIPTION:
Elm 58 3015.08
END DESCRIPTION:
XS GIS Cut Line= 3
      1517798.84      6765126.63      1517955.12      6765026.35
      1518071.15      6764937.39
#Sta/Elev= 30
  4811.7 2261.39  4815.8 2259.55  4830.9 2256.68  4866.5 2247.78  4902.2 2237.63
  4930.7 2232.32  4945.9 2228.32  4951.8 2228.25  4961.1 2225.89  4973.5 2214.78
  4980.2 2214.19  4980.5 2213.69  4984.2 2214.19  4994.3 2216.46  5009.8 2217.91
  5032.3 2227.00  5038.6 2228.29  5046.8 2232.77  5053.1 2233.28  5067.6 2240.90
  5073.9 2239.28  5082.1 2241.81  5088.4 2239.45  5096.6 2241.51  5102.9 2240.87
  5110.6 2243.65  5123.7 2250.47  5132.0 2252.08  5138.3 2256.51  5143.6 2256.15
#Mann=3,-1,0
  4811.7    0.16       0  4980.2    0.07       0  4984.2    0.16       0
Bank Sta=4980.2,4984.2
Exp/Cntr=0.3,0.1

Type RM Length L Ch R = 1,2933,115,115,115
BEGIN DESCRIPTION:
Elm 58 2933.27
END DESCRIPTION:
XS GIS Cut Line= 3
      1517865.27      6765191.71      1518008.51      6765086.24
      1518095.76      6764963.83
#Sta/Elev= 30
  4826.0 2256.77  4828.9 2256.77  4857.1 2250.44  4907.3 2237.42  4921.9 2235.82
  4936.6 2232.39  4957.4 2224.26  4972.0 2216.45  4978.3 2214.34  4984.7 2213.88
  4984.9 2213.38  4988.4 2213.38  4988.7 2213.88  4998.6 2215.40  5007.2 2215.81
  5014.0 2219.50  5021.9 2225.20  5036.7 2232.18  5042.8 2233.97  5050.8 2237.33
  5057.6 2238.73  5063.7 2237.31  5078.5 2238.10  5087.1 2240.81  5093.2 2241.31
  5100.0 2242.92  5128.9 2247.15  5136.8 2249.27  5149.2 2250.77  5154.2 2250.77
#Mann=3,-1,0
  4826.0    0.16       0  4984.7    0.07       0  4988.7    0.16       0
Bank Sta=4984.7,4988.7
Exp/Cntr=0.3,0.1

Type RM Length L Ch R = 1,2818,77,77,77
BEGIN DESCRIPTION:
Elm 58 2818.07
END DESCRIPTION:
XS GIS Cut Line= 3
      1517903.04      6765301.08      1518085.33      6765178.69
      1518117.89      6764974.23
#Sta/Elev= 30
  4771.8 2250.46  4776.0 2250.46  4783.2 2247.03  4789.3 2248.39  4798.2 2245.99
  4804.3 2247.69  4819.2 2243.45  4840.3 2242.01  4855.3 2238.03  4861.3 2240.30
  4897.3 2236.27  4906.3 2233.87  4918.7 2221.05  4927.3 2217.25  4933.3 2211.82
  4954.8 2207.46  4978.3 2205.77  4984.3 2208.88  4986.2 2205.72  4986.4 2205.22
  4990.2 2205.72  4994.2 2205.72  5012.3 2216.96  5032.6 2226.79  5042.7 2228.97
  5062.9 2232.04  5103.5 2232.47  5148.6 2241.32  5154.1 2244.06  5198.4 2250.61
#Mann=3,-1,0
  4771.8    0.16       0  4986.2    0.07       0  4990.2    0.16       0
Bank Sta=4986.2,4990.2
Exp/Cntr=0.3,0.1

Type RM Length L Ch R = 1,2741,48,48,48
BEGIN DESCRIPTION:
Elm 58 2741.23
END DESCRIPTION:
XS GIS Cut Line= 3
      1518059.27      6765476.90      1518140.02      6765269.83
      1518150.43      6764954.76
#Sta/Elev= 30
  4731.8 2261.66  4734.9 2263.91  4752.1 2255.87  4759.4 2250.80  4764.8 2252.74
  4783.9 2243.21  4789.3 2244.22  4795.0 2241.38  4805.8 2239.34  4813.7 2238.18
  4843.6 2241.12  4849.0 2242.93  4868.1 2239.85  4873.5 2241.04  4898.0 2234.55
  4903.3 2235.45  4922.5 2230.62  4927.8 2231.02  4952.3 2221.77  4965.9 2220.41
  4975.9 2222.67  5003.9 2218.85  5004.2 2218.35  5007.9 2218.85  5035.9 2225.43
  5116.0 2226.58  5176.0 2240.03  5216.0 2243.40  5253.6 2250.43  5269.3 2251.26
#Mann=3,-1,0
  4731.8    0.16       0  5003.9    0.07       0  5007.9    0.16       0
Bank Sta=5003.9,5007.9
Exp/Cntr=0.3,0.1

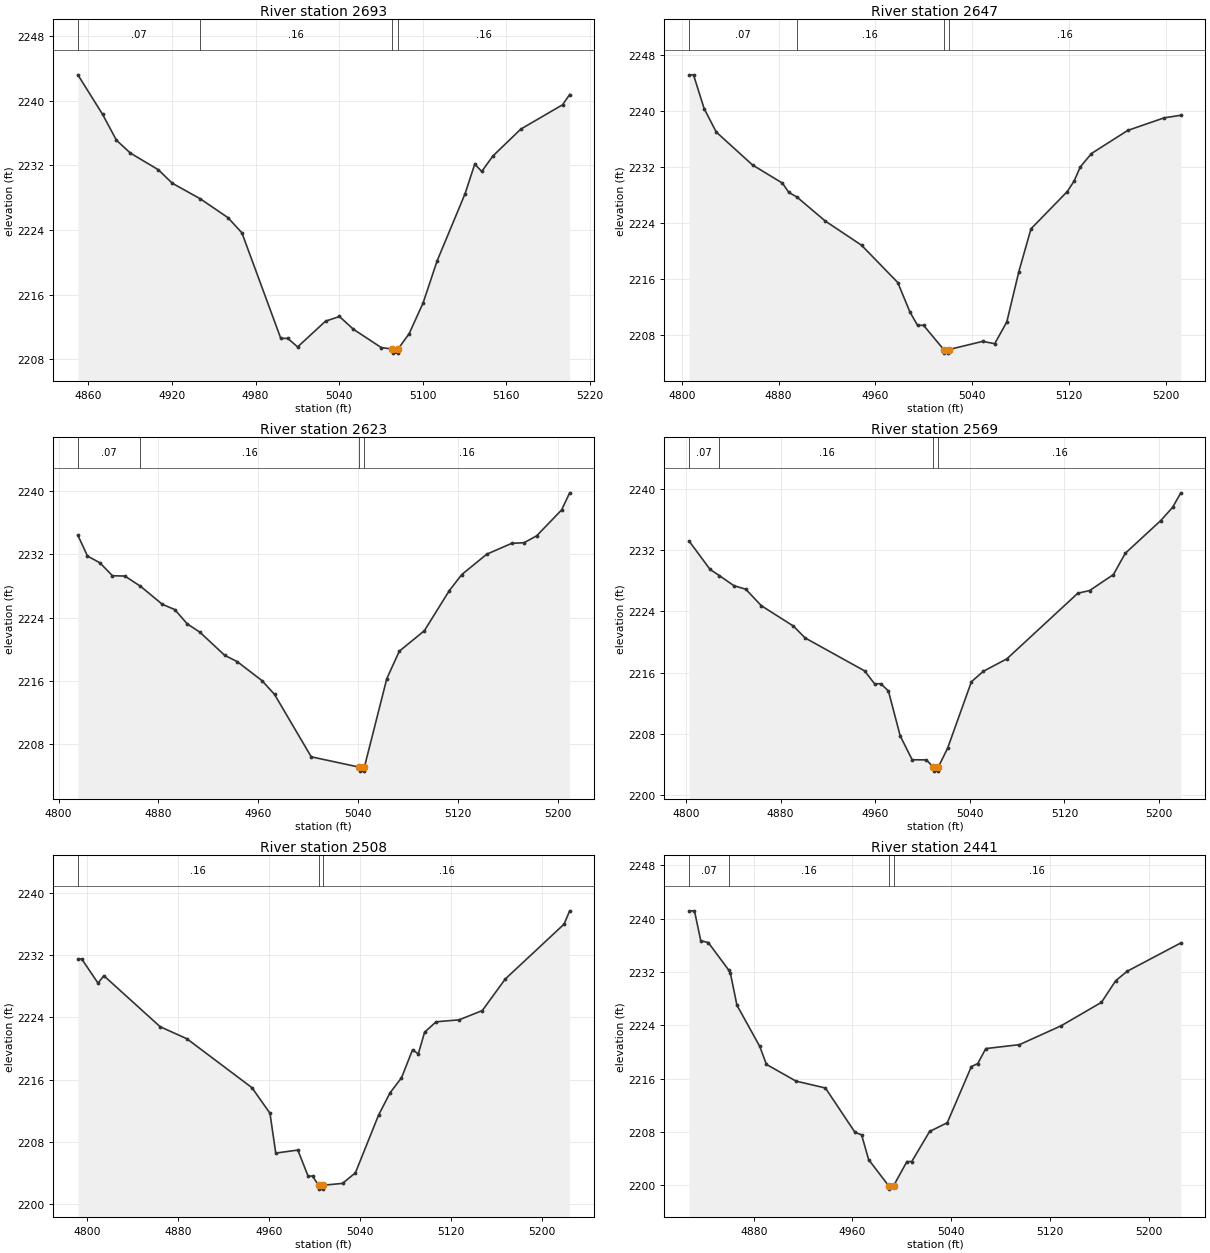
Type RM Length L Ch R = 1,2693,46,46,46
BEGIN DESCRIPTION:
Elm 58 2693.18
END DESCRIPTION:
XS GIS Cut Line= 3
      1518188.19      6765385.67      1518185.59      6765237.28
      1518192.10      6765032.90
#Sta/Elev= 30
  4852.5 2243.23  4870.2 2238.34  4880.2 2235.12  4890.2 2233.53  4910.2 2231.47
  4920.2 2229.80  4940.3 2227.87  4960.2 2225.53  4970.2 2223.65  4998.1 2210.57
  5003.1 2210.57  5010.2 2209.51  5030.2 2212.70  5040.2 2213.28  5050.2 2211.70
  5070.2 2209.43  5078.2 2209.24  5078.5 2208.74  5082.0 2208.74  5082.2 2209.24
  5090.2 2211.15  5100.2 2214.95  5110.3 2220.18  5130.3 2228.48  5137.3 2232.17
  5142.3 2231.25  5150.3 2233.17  5170.3 2236.50  5200.3 2239.52  5205.4 2240.79
#Mann=4,-1,0
  4852.5    0.07       0  4940.3    0.16       0  5078.2    0.07       0
  5082.2    0.16       0
Bank Sta=5078.2,5082.2
Exp/Cntr=0.3,0.1

Type RM Length L Ch R = 1,2647,24,24,24
BEGIN DESCRIPTION:
Elm 58 2647.3
END DESCRIPTION:
XS GIS Cut Line= 3
      1518216.84      6765410.46      1518224.65      6765220.36
      1518216.84      6765004.16
#Sta/Elev= 30
  4806.0 2245.19  4809.7 2245.19  4818.5 2240.35  4828.5 2237.01  4858.5 2232.30
  4883.2 2229.71  4888.5 2228.38  4895.2 2227.72  4918.6 2224.29  4948.6 2220.83
  4978.6 2215.49  4988.6 2211.29  4994.9 2209.38  4999.9 2209.38  5016.6 2205.90
  5016.9 2205.40  5020.4 2205.40  5020.6 2205.90  5048.7 2207.08  5058.7 2206.75
  5068.7 2209.85  5078.7 2217.07  5088.7 2223.17  5118.7 2228.50  5124.4 2230.01
  5129.4 2232.00  5138.7 2233.94  5168.7 2237.24  5198.8 2239.04  5212.6 2239.41
#Mann=4,-1,0
  4806.0    0.07       0  4895.2    0.16       0  5016.6    0.07       0
  5020.6    0.16       0
Bank Sta=5016.6,5020.6
Exp/Cntr=0.3,0.1

Type RM Length L Ch R = 1,2623,54,54,54
BEGIN DESCRIPTION:
Elm 58 2623.34
END DESCRIPTION:
XS GIS Cut Line= 3
      1518240.28      6765385.71      1518242.88      6765194.31
      1518248.05      6764991.49
#Sta/Elev= 30
  4815.4 2234.42  4823.1 2231.79  4833.1 2230.93  4843.1 2229.30  4853.1 2229.26
  4865.6 2227.97  4883.1 2225.69  4893.1 2225.02  4903.1 2223.21  4913.1 2222.18
  4933.1 2219.24  4943.1 2218.45  4963.1 2216.03  4973.1 2214.29  5002.5 2206.41
  5041.1 2205.10  5041.4 2204.60  5044.9 2204.60  5045.1 2205.10  5063.1 2216.30
  5073.1 2219.76  5093.2 2222.35  5113.2 2227.42  5123.2 2229.45  5143.2 2232.02
  5163.2 2233.39  5173.2 2233.48  5183.2 2234.34  5203.2 2237.61  5209.7 2239.78
#Mann=4,-1,0
  4815.4    0.07       0  4865.6    0.16       0  5041.1    0.07       0
  5045.1    0.16       0
Bank Sta=5041.1,5045.1
Exp/Cntr=0.3,0.1

Type RM Length L Ch R = 1,2569,61,61,61
BEGIN DESCRIPTION:
Elm 58 2569.46
END DESCRIPTION:
XS GIS Cut Line= 3
      1518274.13      6765385.76      1518293.66      6765189.11
      1518284.63      6764971.02
#Sta/Elev= 30
  4802.5 2233.21  4820.3 2229.49  4828.1 2228.69  4840.4 2227.37  4850.5 2226.90
  4863.7 2224.74  4890.7 2222.09  4900.7 2220.53  4951.0 2216.22  4959.5 2214.52
  4964.6 2214.55  4971.1 2213.60  4981.1 2207.71  4991.2 2204.60  5003.2 2204.58
  5009.2 2203.61  5009.5 2203.11  5013.0 2203.11  5013.2 2203.61  5021.2 2206.12
  5041.3 2214.80  5051.3 2216.16  5071.3 2217.80  5131.3 2226.38  5141.3 2226.73
  5161.4 2228.82  5171.4 2231.60  5201.4 2235.88  5211.4 2237.60  5218.4 2239.51
#Mann=4,-1,0
  4802.5    0.07       0  4828.1    0.16       0  5009.2    0.07       0
  5013.2    0.16       0
Bank Sta=5009.2,5013.2
Exp/Cntr=0.3,0.1

Type RM Length L Ch R = 1,2508,67,67,67
BEGIN DESCRIPTION:
Elm 58 2507.87
END DESCRIPTION:
XS GIS Cut Line= 3
      1518327.52      6765389.61      1518354.86      6765185.20
      1518318.55      6764962.17
#Sta/Elev= 30
  4791.8 2231.54  4795.1 2231.54  4809.5 2228.41  4814.6 2229.37  4864.1 2222.80
  4887.6 2221.25  4944.8 2214.95  4960.6 2211.66  4965.7 2206.53  4985.1 2206.92
  4994.1 2203.57  4998.0 2203.57  5003.3 2202.39  5003.6 2201.89  5007.1 2201.89
  5007.3 2202.39  5024.4 2202.63  5035.7 2203.99  5056.0 2211.40  5066.1 2214.28
  5076.2 2216.22  5085.9 2219.82  5091.0 2219.31  5096.5 2222.09  5106.6 2223.43
  5126.9 2223.69  5147.2 2224.88  5167.4 2228.94  5219.1 2236.01  5224.0 2237.72
#Mann=3,-1,0
  4791.8    0.16       0  5003.3    0.07       0  5007.3    0.16       0
Bank Sta=5003.3,5007.3
Exp/Cntr=0.3,0.1

Type RM Length L Ch R = 1,2441,63,63,63
BEGIN DESCRIPTION:
Elm 58 2441.04
END DESCRIPTION:
XS GIS Cut Line= 3
      1518473.36      6765302.42      1518404.34      6765135.72
      1518344.46      6764926.13
#Sta/Elev= 30
  4827.6 2241.15  4832.0 2241.15  4837.1 2236.67  4843.2 2236.40  4859.7 2232.28
  4861.0 2231.89  4866.4 2227.01  4884.9 2220.83  4890.3 2218.14  4914.2 2215.64
  4938.1 2214.60  4962.0 2207.97  4967.4 2207.58  4973.1 2203.87  4989.3 2199.95
  4989.5 2199.45  4993.3 2199.95  5004.1 2203.58  5008.0 2203.58  5022.5 2208.09
  5036.8 2209.40  5056.3 2217.81  5061.5 2218.27  5068.0 2220.51  5095.3 2221.10
  5129.1 2223.93  5161.7 2227.44  5173.3 2230.69  5182.5 2232.09  5226.0 2236.34
#Mann=4,-1,0
  4827.6    0.07       0  4859.7    0.16       0  4989.3    0.07       0
  4993.3    0.16       0
Bank Sta=4989.3,4993.3
Exp/Cntr=0.3,0.1

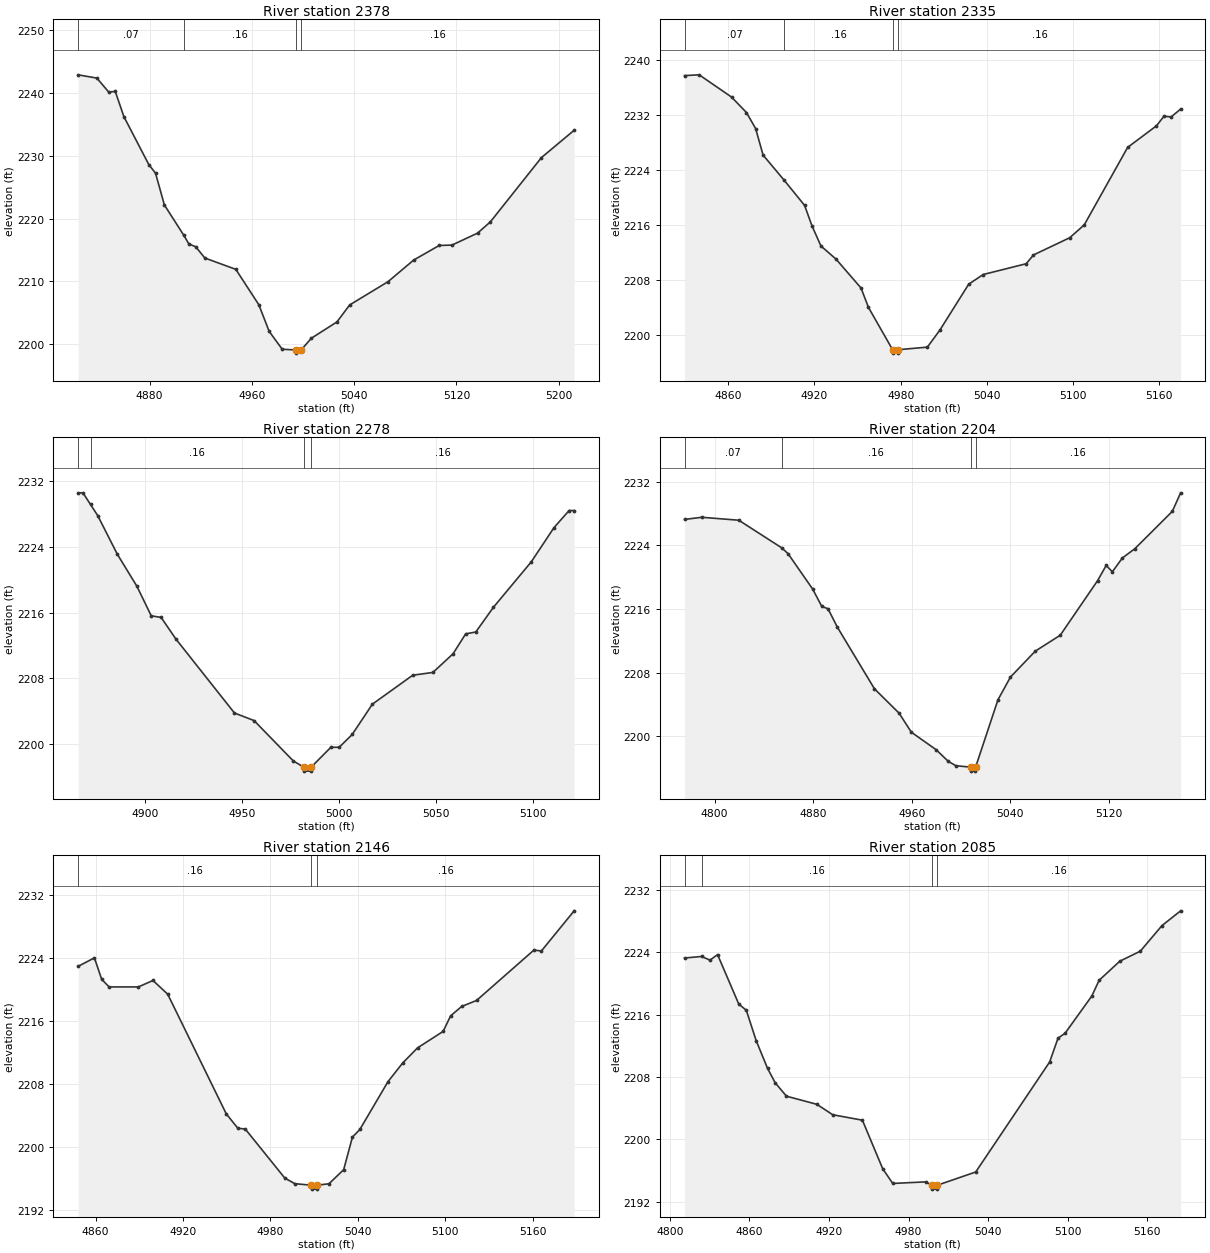
Type RM Length L Ch R = 1,2378,43,43,43
BEGIN DESCRIPTION:
Elm 58 2377.86
END DESCRIPTION:
XS GIS Cut Line= 3
      1518518.91      6765291.93      1518466.84      6765138.32
      1518464.24      6764912.43
#Sta/Elev= 30
  4824.0 2242.87  4838.7 2242.35  4847.9 2240.14  4853.1 2240.22  4859.8 2236.23
  4879.3 2228.60  4884.6 2227.21  4891.5 2222.17  4906.7 2217.34  4910.7 2215.95
  4916.0 2215.52  4923.2 2213.72  4947.4 2211.92  4965.4 2206.29  4973.5 2202.05
  4983.7 2199.21  4994.5 2199.09  4994.8 2198.59  4998.5 2199.09  5006.5 2200.96
  5026.5 2203.55  5036.5 2206.26  5066.5 2209.96  5086.5 2213.39  5106.5 2215.72
  5116.5 2215.78  5136.5 2217.68  5146.5 2219.46  5186.5 2229.70  5212.1 2234.05
#Mann=4,-1,0
  4824.0    0.07       0  4906.7    0.16       0  4994.5    0.07       0
  4998.5    0.16       0
Bank Sta=4994.5,4998.5
Exp/Cntr=0.3,0.1

Type RM Length L Ch R = 1,2335,57,57,57
BEGIN DESCRIPTION:
Elm 58 2334.97
END DESCRIPTION:
XS GIS Cut Line= 3
      1518543.68      6765259.46      1518498.09      6765096.66
      1518478.75      6764921.29
#Sta/Elev= 30
  4829.5 2237.77  4839.7 2237.88  4862.2 2234.65  4872.6 2232.40  4879.0 2230.07
  4884.2 2226.21  4898.9 2222.55  4913.1 2218.90  4918.3 2215.90  4924.5 2212.99
  4934.9 2211.11  4952.4 2206.89  4957.6 2204.06  4974.4 2197.92  4974.7 2197.42
  4978.2 2197.42  4978.4 2197.92  4998.6 2198.29  5007.3 2200.76  5027.4 2207.44
  5037.5 2208.85  5067.5 2210.42  5072.5 2211.69  5097.8 2214.20  5107.9 2216.07
  5138.1 2227.33  5158.2 2230.47  5163.4 2231.86  5168.4 2231.76  5175.0 2232.90
#Mann=4,-1,0
  4829.5    0.07       0  4898.9    0.16       0  4974.4    0.07       0
  4978.4    0.16       0
Bank Sta=4974.4,4978.4
Exp/Cntr=0.3,0.1

Type RM Length L Ch R = 1,2278,74,74,74
BEGIN DESCRIPTION:
Elm 58 2277.643
END DESCRIPTION:
XS GIS Cut Line= 3
      1518555.00      6765188.02      1518538.25      6765054.46
      1518505.00      6764938.02
#Sta/Elev= 30
  4865.4 2230.60  4867.9 2230.60  4871.8 2229.18  4875.5 2227.83  4885.6 2223.12
  4895.7 2219.21  4903.1 2215.60  4908.2 2215.40  4915.8 2212.77  4946.0 2203.74
  4956.1 2202.82  4976.3 2197.90  4981.6 2197.15  4981.9 2196.65  4985.4 2196.65
  4985.6 2197.15  4995.7 2199.56  5000.0 2199.56  5006.7 2201.12  5017.1 2204.82
  5037.9 2208.35  5048.3 2208.69  5058.7 2210.97  5065.2 2213.40  5070.4 2213.62
  5079.5 2216.64  5099.0 2222.18  5110.7 2226.35  5118.5 2228.44  5121.1 2228.44
#Mann=4,-1,0
  4865.4    0.07       0  4871.8    0.16       0  4981.6    0.07       0
  4985.6    0.16       0
Bank Sta=4981.6,4985.6
Exp/Cntr=0.3,0.1

Type RM Length L Ch R = 1,2204,58,58,58
BEGIN DESCRIPTION:
Elm 58 2204.42
END DESCRIPTION:
XS GIS Cut Line= 3
      1518612.67      6765262.02      1518607.47      6765040.67
      1518581.66      6764861.32
#Sta/Elev= 30
  4775.7 2227.24  4789.7 2227.51  4819.7 2227.14  4854.6 2223.67  4859.7 2222.94
  4879.7 2218.49  4887.1 2216.31  4892.1 2216.03  4899.8 2213.69  4929.8 2205.98
  4949.8 2202.92  4959.8 2200.52  4979.8 2198.34  4989.8 2196.86  4995.9 2196.32
  5007.9 2196.14  5008.2 2195.64  5011.7 2195.64  5011.9 2196.14  5030.1 2204.61
  5040.2 2207.45  5060.4 2210.71  5080.6 2212.70  5110.9 2219.55  5117.9 2221.46
  5122.9 2220.67  5131.1 2222.41  5141.2 2223.57  5171.6 2228.26  5178.3 2230.58
#Mann=4,-1,0
  4775.7    0.07       0  4854.6    0.16       0  5007.9    0.07       0
  5011.9    0.16       0
Bank Sta=5007.9,5011.9
Exp/Cntr=0.3,0.1

Type RM Length L Ch R = 1,2146,61,61,61
BEGIN DESCRIPTION:
Elm 58 2145.63
END DESCRIPTION:
XS GIS Cut Line= 3
      1518681.69      6765189.14      1518666.06      6765039.37
      1518636.31      6764851.79
#Sta/Elev= 30
  4848.0 2222.88  4859.2 2223.96  4864.2 2221.23  4869.3 2220.27  4889.4 2220.27
  4899.4 2221.09  4909.5 2219.35  4949.7 2204.16  4957.7 2202.32  4962.7 2202.24
  4989.9 2196.00  4996.8 2195.29  5008.1 2195.10  5008.3 2194.60  5011.8 2194.60
  5012.1 2195.10  5020.2 2195.28  5030.3 2197.07  5036.3 2201.20  5041.4 2202.17
  5060.7 2208.24  5070.8 2210.61  5081.0 2212.53  5098.6 2214.63  5103.7 2216.60
  5111.3 2217.79  5121.5 2218.55  5160.9 2224.95  5166.0 2224.83  5188.5 2229.93
#Mann=3,-1,0
  4848.0    0.16       0  5008.1    0.07       0  5012.1    0.16       0
Bank Sta=5008.1,5012.1
Exp/Cntr=0.3,0.1

Type RM Length L Ch R = 1,2085,52,52,52
BEGIN DESCRIPTION:
Elm 58 2084.65
END DESCRIPTION:
XS GIS Cut Line= 3
      1518882.21      6765114.89      1518723.35      6765026.35
      1518659.78      6764844.71
#Sta/Elev= 30
  4811.0 2223.27  4823.8 2223.47  4830.2 2223.00  4835.9 2223.71  4851.9 2217.36
  4857.6 2216.56  4865.0 2212.68  4873.6 2209.11  4879.4 2207.25  4887.9 2205.53
  4910.8 2204.49  4922.8 2203.15  4945.2 2202.45  4960.5 2196.22  4968.1 2194.33
  4992.9 2194.53  4997.7 2194.10  4998.0 2193.60  5001.5 2193.60  5001.7 2194.10
  5030.7 2195.80  5086.5 2209.93  5092.8 2212.98  5098.1 2213.61  5118.3 2218.39
  5123.8 2220.41  5139.4 2222.86  5154.9 2224.15  5171.2 2227.43  5185.3 2229.33
#Mann=4,-1,0
  4811.0    0.07       0  4823.8    0.16       0  4997.7    0.07       0
  5001.7    0.16       0
Bank Sta=4997.7,5001.7
Exp/Cntr=0.3,0.1

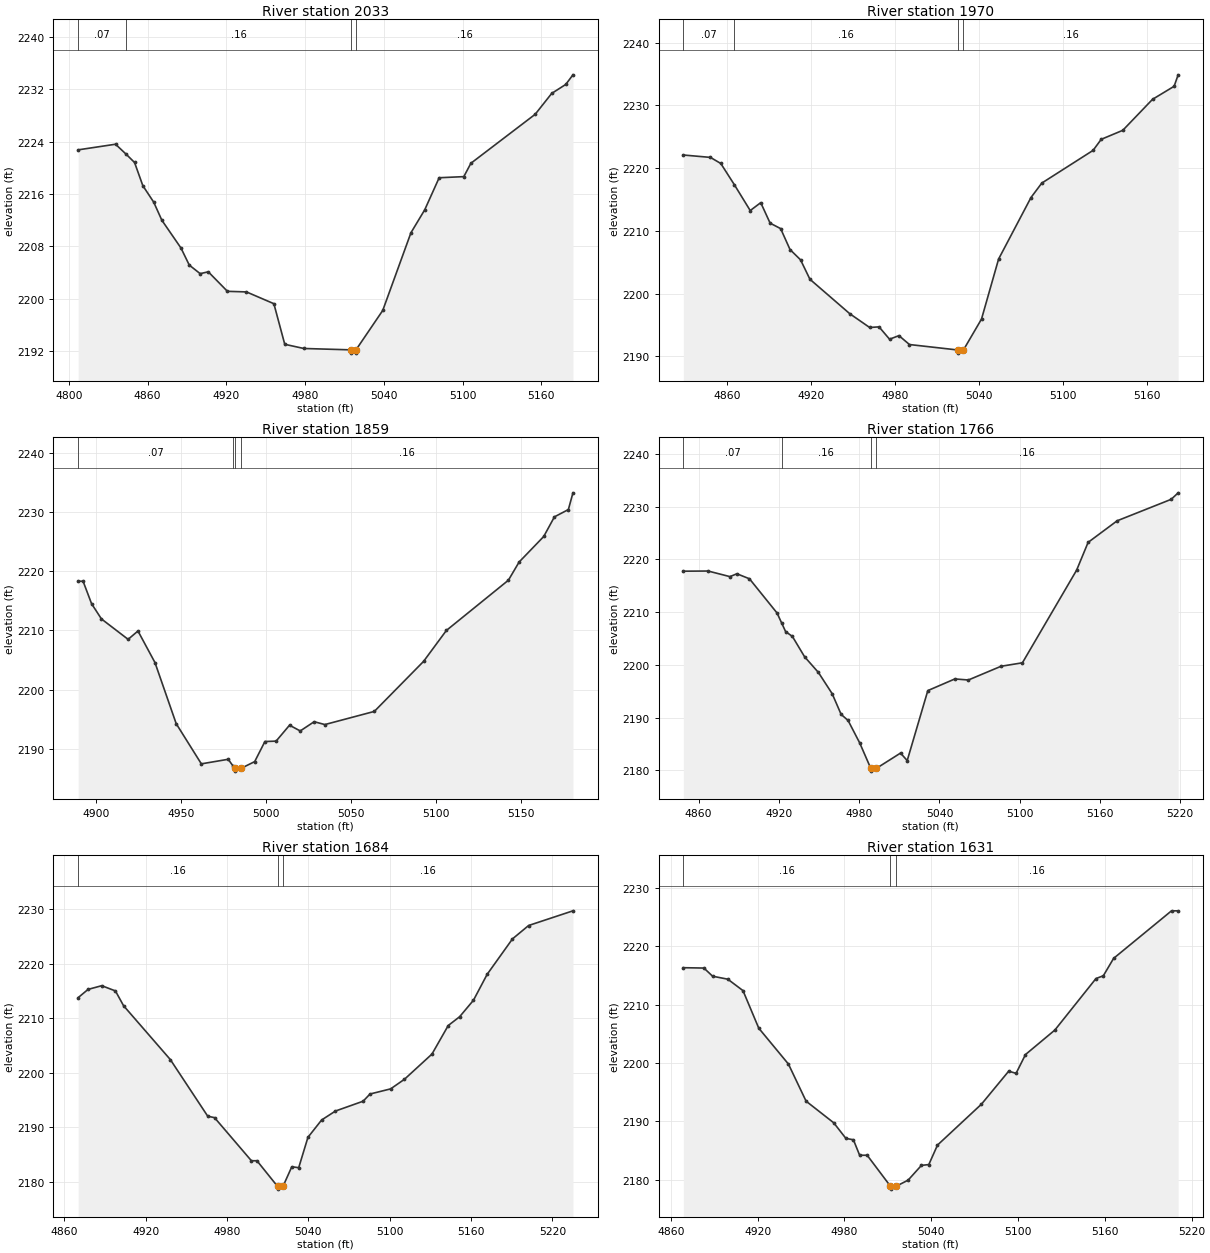
Type RM Length L Ch R = 1,2033,63,63,63
BEGIN DESCRIPTION:
Elm 58 2033.23
END DESCRIPTION:
XS GIS Cut Line= 3
      1518912.16      6765100.57      1518757.21      6764983.38
      1518690.84      6764812.92
#Sta/Elev= 30
  4807.0 2222.75  4835.5 2223.61  4843.6 2222.08  4850.0 2220.82  4856.3 2217.28
  4864.6 2214.76  4870.8 2212.00  4885.4 2207.75  4891.7 2205.15  4900.0 2203.84
  4906.2 2204.12  4920.8 2201.14  4935.3 2201.05  4956.2 2199.25  4964.5 2193.05
  4979.0 2192.41  5014.8 2192.20  5015.0 2191.70  5018.5 2191.70  5018.8 2192.20
  5039.2 2198.22  5060.7 2210.09  5071.2 2213.59  5082.2 2218.49  5101.0 2218.66
  5106.4 2220.70  5155.4 2228.18  5168.0 2231.37  5178.7 2232.74  5184.2 2234.21
#Mann=4,-1,0
  4807.0    0.07       0  4843.6    0.16       0  5014.8    0.07       0
  5018.8    0.16       0
Bank Sta=5014.8,5018.8
Exp/Cntr=0.3,0.1

Type RM Length L Ch R = 1,1970,111,111,111
BEGIN DESCRIPTION:
Elm 58 1970.28
END DESCRIPTION:
XS GIS Cut Line= 3
      1518919.94      6765070.59      1518805.38      6764943.01
      1518709.52      6764788.85
#Sta/Elev= 30
  4829.0 2222.10  4848.3 2221.72  4855.7 2220.75  4865.3 2217.39  4876.7 2213.24
  4884.2 2214.50  4890.9 2211.23  4898.4 2210.36  4905.1 2207.02  4912.6 2205.38
  4919.3 2202.28  4947.7 2196.79  4961.9 2194.59  4968.6 2194.69  4976.1 2192.72
  4982.8 2193.29  4990.3 2191.87  5024.8 2191.00  5025.1 2190.50  5028.8 2191.00
  5041.7 2195.93  5053.9 2205.51  5077.0 2215.32  5084.7 2217.62  5121.3 2222.84
  5127.1 2224.60  5142.5 2226.04  5163.7 2230.98  5179.1 2233.06  5182.0 2234.89
#Mann=4,-1,0
  4829.0    0.07       0  4865.3    0.16       0  5024.8    0.07       0
  5028.8    0.16       0
Bank Sta=5024.8,5028.8
Exp/Cntr=0.3,0.1

Type RM Length L Ch R = 1,1859,93,93,93
BEGIN DESCRIPTION:
Elm 58 1858.778
END DESCRIPTION:
XS GIS Cut Line= 3
      1518955.00      6764988.01      1518899.65      6764892.14
      1518789.89      6764748.84
#Sta/Elev= 30
  4889.3 2218.31  4892.2 2218.31  4897.2 2214.51  4903.0 2211.94  4918.7 2208.49
  4924.5 2209.90  4934.5 2204.57  4947.0 2194.24  4961.8 2187.45  4977.6 2188.22
  4980.3 2187.15  4981.4 2186.72  4981.6 2186.22  4985.4 2186.72  4993.2 2187.83
  4999.2 2191.22  5005.8 2191.29  5013.7 2193.98  5020.0 2193.01  5028.2 2194.57
  5034.5 2194.09  5063.6 2196.31  5092.6 2204.77  5106.0 2209.99  5142.5 2218.48
  5148.8 2221.55  5163.3 2225.87  5169.6 2229.19  5177.8 2230.42  5180.5 2233.25
#Mann=4,-1,0
  4889.3    0.07       0  4980.3    0.16       0  4981.4    0.07       0
  4985.4    0.16       0
Bank Sta=4981.4,4985.4
Exp/Cntr=0.3,0.1

Type RM Length L Ch R = 1,1766,82,82,82
BEGIN DESCRIPTION:
Elm 58 1766.36
END DESCRIPTION:
XS GIS Cut Line= 3
      1519008.51      6764985.99      1518972.05      6764837.54
      1518940.82      6764622.86
#Sta/Elev= 30
  4848.6 2217.75  4867.1 2217.78  4883.4 2216.72  4888.6 2217.26  4898.0 2216.31
  4918.6 2209.83  4922.1 2207.91  4925.0 2206.31  4930.1 2205.38  4939.2 2201.53
  4949.5 2198.57  4959.8 2194.54  4966.5 2190.62  4971.7 2189.46  4980.4 2185.20
  4988.7 2180.36  4988.9 2179.86  4992.7 2180.36  5010.9 2183.28  5015.9 2181.86
  5031.3 2195.12  5051.5 2197.33  5061.6 2197.13  5086.0 2199.73  5102.0 2200.39
  5142.5 2217.94  5151.1 2223.21  5172.8 2227.30  5213.2 2231.37  5218.4 2232.60
#Mann=4,-1,0
  4848.6    0.07       0  4922.1    0.16       0  4988.7    0.07       0
  4992.7    0.16       0
Bank Sta=4988.7,4992.7
Exp/Cntr=0.3,0.1

Type RM Length L Ch R = 1,1684,53,53,53
BEGIN DESCRIPTION:
Elm 58 1683.6
END DESCRIPTION:
XS GIS Cut Line= 3
      1519034.55      6764965.16      1519055.38      6764834.94
      1519012.42      6764605.81
#Sta/Elev= 30
  4870.2 2213.78  4877.5 2215.29  4887.6 2215.97  4897.7 2215.01  4903.7 2212.30
  4938.2 2202.43  4965.8 2192.05  4970.8 2191.79  4998.0 2183.89  5002.1 2183.89
  5017.3 2179.19  5017.6 2178.69  5021.3 2179.19  5027.8 2182.79  5032.9 2182.62
  5039.7 2188.18  5049.8 2191.36  5060.0 2193.00  5080.4 2194.80  5085.5 2196.12
  5100.7 2197.06  5110.9 2198.82  5131.2 2203.44  5143.2 2208.67  5151.6 2210.28
  5161.8 2213.30  5171.9 2218.05  5190.6 2224.55  5202.5 2227.00  5235.2 2229.69
#Mann=3,-1,0
  4870.2    0.16       0  5017.3    0.07       0  5021.3    0.16       0
Bank Sta=5017.3,5021.3
Exp/Cntr=0.3,0.1

Type RM Length L Ch R = 1,1631,67,67,67
BEGIN DESCRIPTION:
Elm 58 1631.4
END DESCRIPTION:
XS GIS Cut Line= 3
      1519143.93      6764957.35      1519107.47      6764838.85
      1519071.01      6764624.01
#Sta/Elev= 30
  4868.7 2216.36  4882.9 2216.30  4888.9 2214.90  4899.4 2214.39  4909.9 2212.43
  4920.8 2205.99  4941.3 2199.84  4953.5 2193.48  4972.6 2189.77  4981.0 2187.10
  4986.2 2186.86  4990.5 2184.21  4995.7 2184.21  5011.8 2178.90  5012.1 2178.40
  5015.8 2178.90  5024.0 2179.94  5033.2 2182.47  5038.3 2182.61  5044.3 2185.95
  5074.7 2192.97  5093.5 2198.62  5098.6 2198.25  5105.1 2201.47  5125.4 2205.67
  5153.8 2214.50  5158.9 2214.98  5166.0 2217.96  5206.0 2226.11  5210.6 2226.11
#Mann=3,-1,0
  4868.7    0.16       0  5011.8    0.07       0  5015.8    0.16       0
Bank Sta=5011.8,5015.8
Exp/Cntr=0.3,0.1