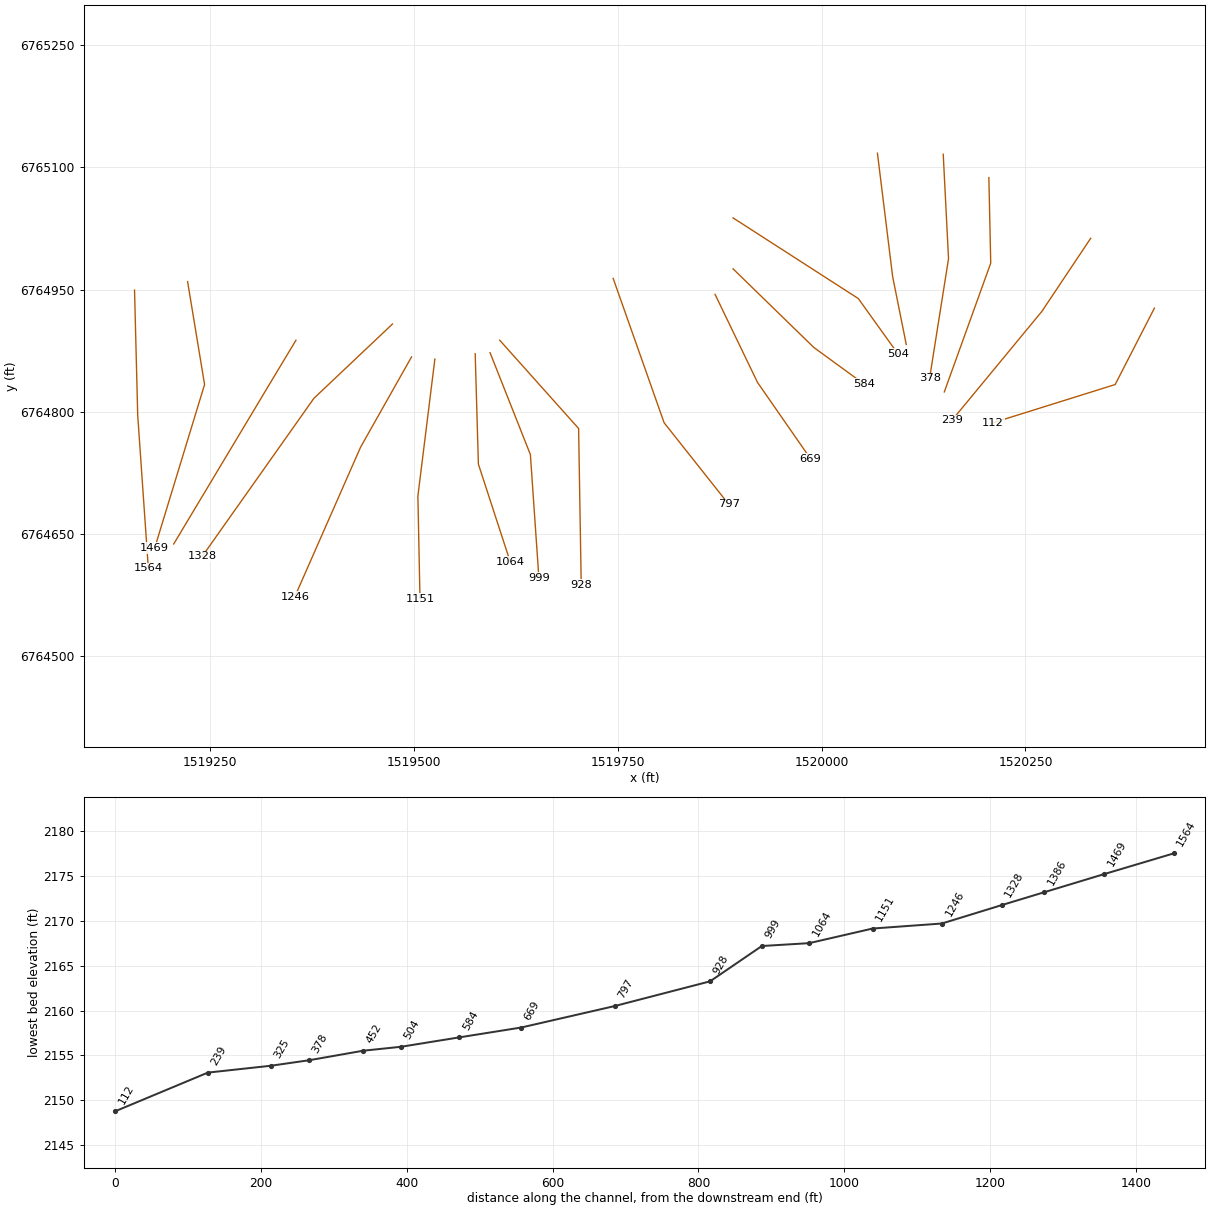
HEC-RAS study Elm 58.prj: Elm 58 Base Level Engineering

--- Elm 58.g01 (geometry) --- (continued)

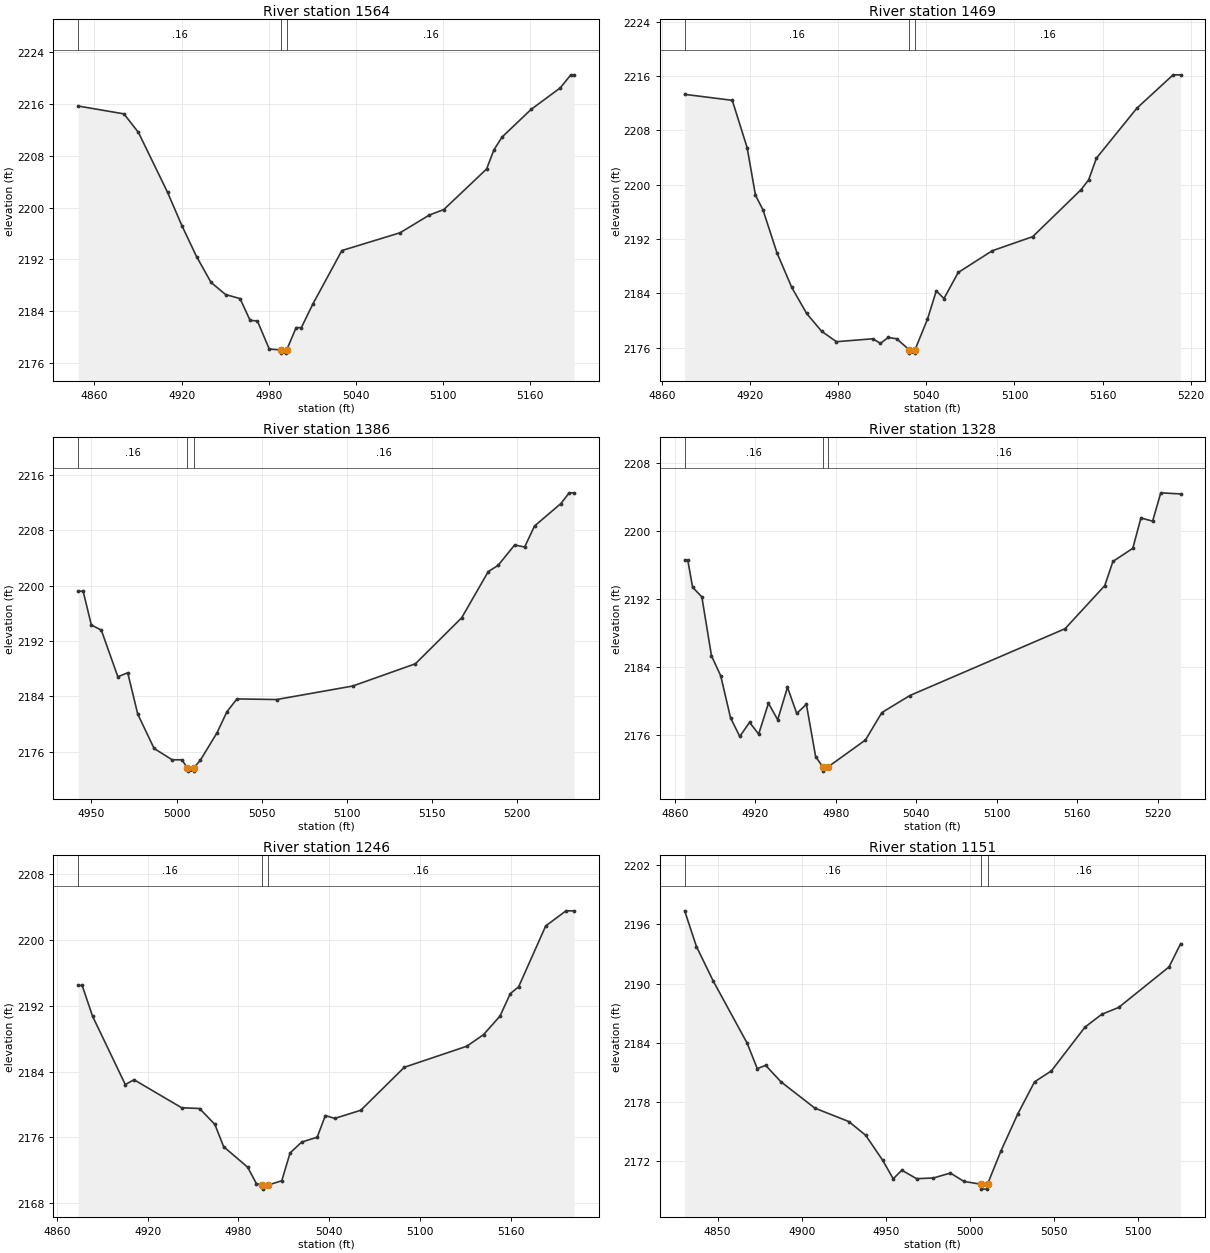
Type RM Length L Ch R = 1,1564,95,95,95
BEGIN DESCRIPTION:
Elm 58 1563.72
END DESCRIPTION:
XS GIS Cut Line= 3
      1519156.95      6764949.51      1519160.85      6764795.88
      1519173.87      6764608.41
#Sta/Elev= 30
  4848.8 2215.69  4880.3 2214.48  4890.3 2211.61  4910.3 2202.38  4920.3 2197.18
  4930.3 2192.45  4940.3 2188.45  4950.3 2186.58  4960.3 2185.95  4967.2 2182.58
  4972.2 2182.51  4980.4 2178.16  4988.4 2178.03  4988.6 2177.53  4992.1 2177.53
  4992.4 2178.03  4998.9 2181.47  5002.5 2181.47  5010.4 2185.11  5030.4 2193.37
  5070.5 2196.12  5090.6 2198.85  5100.6 2199.70  5130.1 2205.97  5135.1 2208.90
  5140.7 2210.89  5160.7 2215.16  5180.8 2218.49  5188.1 2220.51  5190.4 2220.51
#Mann=3,-1,0
  4848.8    0.16       0  4988.4    0.07       0  4992.4    0.16       0
Bank Sta=4988.4,4992.4
Exp/Cntr=0.3,0.1

Type RM Length L Ch R = 1,1469,83,83,83
BEGIN DESCRIPTION:
Elm 58 1469.32
END DESCRIPTION:
XS GIS Cut Line= 3
      1519222.05      6764959.92      1519242.88      6764833.64
      1519181.70      6764633.15
#Sta/Elev= 30
  4875.5 2213.29  4907.9 2212.41  4918.0 2205.46  4923.7 2198.45  4928.8 2196.30
  4938.3 2190.00  4948.4 2184.89  4958.5 2181.07  4968.7 2178.45  4978.8 2176.91
  5003.5 2177.34  5008.8 2176.67  5014.0 2177.53  5019.8 2177.34  5028.3 2175.73
  5028.5 2175.23  5032.0 2175.23  5032.3 2175.73  5040.7 2180.18  5046.8 2184.39
  5052.0 2183.26  5061.7 2187.09  5084.8 2190.28  5112.4 2192.36  5145.2 2199.24
  5150.5 2200.72  5155.8 2203.91  5183.3 2211.25  5208.0 2216.16  5213.1 2216.16
#Mann=3,-1,0
  4875.5    0.16       0  5028.3    0.07       0  5032.3    0.16       0
Bank Sta=5028.3,5032.3
Exp/Cntr=0.3,0.1

Type RM Length L Ch R = 1,1386,58,58,58
BEGIN DESCRIPTION:
Elm 58 1386.461
END DESCRIPTION:
XS GIS Cut Line= 3
      1519354.99      6764887.98      1519325.17      6764838.46
      1519205.01      6764638.02
#Sta/Elev= 30
  4942.2 2199.20  4945.1 2199.20  4949.9 2194.33  4955.8 2193.56  4965.5 2186.83
  4971.3 2187.41  4977.2 2181.43  4986.8 2176.47  4997.4 2174.83  5003.2 2174.83
  5006.2 2173.69  5006.5 2173.19  5010.0 2173.19  5010.2 2173.69  5014.0 2174.77
  5023.8 2178.74  5029.6 2181.77  5035.5 2183.63  5058.8 2183.54  5103.5 2185.49
  5140.4 2188.71  5167.6 2195.36  5183.2 2202.03  5189.0 2202.93  5198.7 2205.88
  5204.6 2205.59  5210.4 2208.62  5225.9 2211.87  5230.8 2213.42  5233.7 2213.42
#Mann=3,-1,0
  4942.2    0.16       0  5006.2    0.07       0  5010.2    0.16       0
Bank Sta=5006.2,5010.2
Exp/Cntr=0.3,0.1

Type RM Length L Ch R = 1,1328,82,82,82
BEGIN DESCRIPTION:
Elm 58 1328.35
END DESCRIPTION:
XS GIS Cut Line= 3
      1519473.38      6764907.88      1519377.00      6764816.71
      1519240.04      6764622.89
#Sta/Elev= 30
  4867.2 2196.56  4869.5 2196.56  4873.1 2193.36  4880.0 2192.23  4887.2 2185.31
  4894.1 2182.95  4901.4 2178.03  4908.3 2175.83  4915.6 2177.49  4922.4 2176.11
  4929.7 2179.74  4936.6 2177.79  4943.9 2181.61  4950.8 2178.54  4958.0 2179.61
  4964.9 2173.47  4970.2 2172.26  4970.4 2171.76  4974.2 2172.26  5002.1 2175.42
  5014.3 2178.64  5035.2 2180.64  5151.0 2188.49  5180.6 2193.55  5186.7 2196.39
  5201.5 2197.93  5207.6 2201.50  5216.3 2201.12  5222.4 2204.45  5237.2 2204.32
#Mann=3,-1,0
  4867.2    0.16       0  4970.2    0.07       0  4974.2    0.16       0
Bank Sta=4970.2,4974.2
Exp/Cntr=0.3,0.1

Type RM Length L Ch R = 1,1246,95,95,95
BEGIN DESCRIPTION:
Elm 58 1245.83
END DESCRIPTION:
XS GIS Cut Line= 3
      1519496.79      6764867.49      1519434.29      6764756.81
      1519353.54      6764573.18
#Sta/Elev= 30
  4874.1 2194.48  4876.7 2194.48  4883.6 2190.73  4905.2 2182.43  4911.0 2183.01
  4942.4 2179.61  4954.3 2179.51  4964.4 2177.58  4970.2 2174.87  4986.1 2172.37
  4991.8 2170.39  4995.6 2170.21  4995.9 2169.71  4999.6 2170.21  5008.6 2170.73
  5014.1 2174.11  5021.8 2175.44  5032.0 2176.02  5037.4 2178.66  5043.6 2178.31
  5060.8 2179.30  5089.6 2184.53  5130.8 2187.08  5141.9 2188.49  5152.8 2190.75
  5159.6 2193.48  5165.1 2194.31  5183.0 2201.71  5196.4 2203.55  5201.8 2203.55
#Mann=3,-1,0
  4874.1    0.16       0  4995.6    0.07       0  4999.6    0.16       0
Bank Sta=4995.6,4999.6
Exp/Cntr=0.3,0.1

Type RM Length L Ch R = 1,1151,87,87,87
BEGIN DESCRIPTION:
Elm 58 1151.36
END DESCRIPTION:
XS GIS Cut Line= 3
      1519525.44      6764864.91      1519504.60      6764696.92
      1519507.17      6764571.12
#Sta/Elev= 30
  4830.4 2197.37  4837.4 2193.75  4847.4 2190.25  4867.6 2183.94  4873.6 2181.37
  4878.6 2181.70  4887.7 2180.03  4907.9 2177.36  4928.1 2176.00  4938.1 2174.61
  4948.2 2172.08  4954.5 2170.20  4959.6 2171.07  4968.4 2170.21  4978.4 2170.28
  4988.5 2170.78  4996.6 2169.93  5006.6 2169.65  5006.8 2169.15  5010.3 2169.15
  5010.6 2169.65  5018.6 2173.03  5028.6 2176.77  5038.6 2180.03  5048.6 2181.14
  5068.6 2185.58  5078.6 2186.88  5088.6 2187.57  5118.6 2191.68  5125.5 2194.04
#Mann=3,-1,0
  4830.4    0.16       0  5006.6    0.07       0  5010.6    0.16       0
Bank Sta=5006.6,5010.6
Exp/Cntr=0.3,0.1

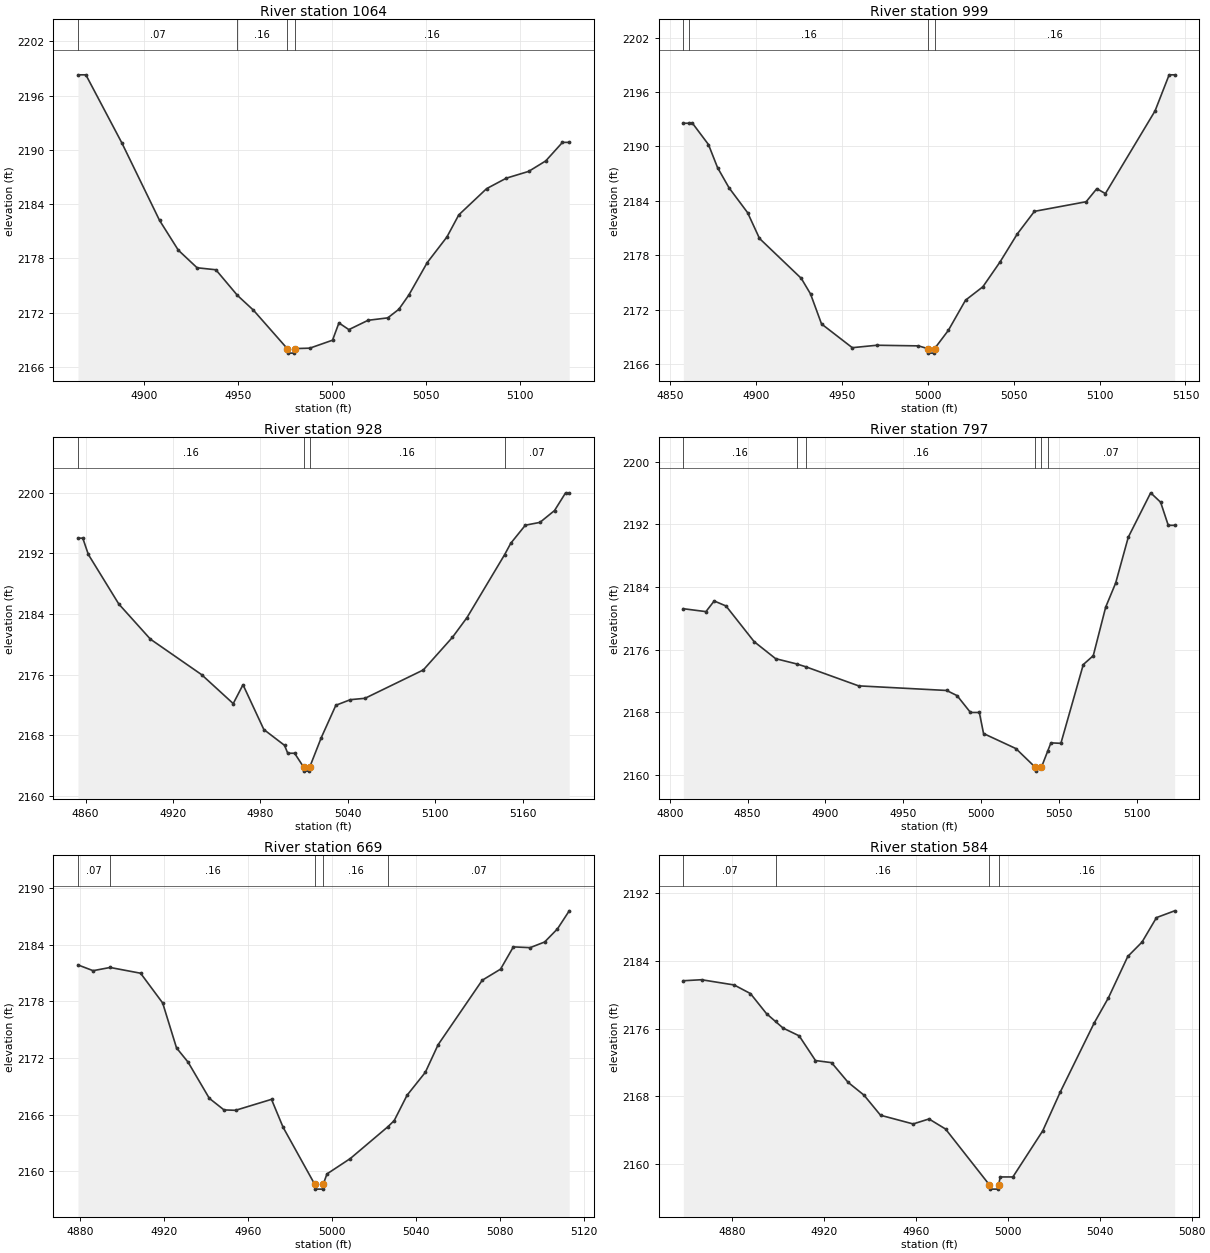
Type RM Length L Ch R = 1,1064,65,65,65
BEGIN DESCRIPTION:
Elm 58 1063.99
END DESCRIPTION:
XS GIS Cut Line= 3
      1519574.91      6764871.39      1519578.82      6764735.98
      1519617.89      6764616.15
#Sta/Elev= 30
  4864.7 2198.30  4868.9 2198.30  4888.1 2190.75  4908.1 2182.21  4918.1 2178.91
  4928.1 2176.96  4938.1 2176.74  4949.6 2173.90  4958.1 2172.27  4976.1 2168.02
  4976.4 2167.52  4979.9 2167.52  4980.1 2168.02  4988.1 2168.07  5000.2 2168.95
  5003.6 2170.86  5008.9 2170.12  5019.1 2171.15  5029.6 2171.42  5035.5 2172.37
  5040.8 2173.94  5050.6 2177.53  5061.1 2180.37  5067.4 2182.81  5082.2 2185.71
  5092.7 2186.87  5104.6 2187.62  5113.7 2188.78  5122.6 2190.83  5126.2 2190.83
#Mann=4,-1,0
  4864.7    0.07       0  4949.6    0.16       0  4976.1    0.07       0
  4980.1    0.16       0
Bank Sta=4976.1,4980.1
Exp/Cntr=0.3,0.1

Type RM Length L Ch R = 1,999,71,71,71
BEGIN DESCRIPTION:
Elm 58 999.44
END DESCRIPTION:
XS GIS Cut Line= 3
      1519593.13      6764872.73      1519642.62      6764747.70
      1519653.04      6764596.63
#Sta/Elev= 30
  4857.8 2192.56  4861.3 2192.56  4863.1 2192.56  4872.4 2190.21  4877.7 2187.66
  4884.4 2185.43  4895.2 2182.69  4902.1 2179.85  4926.4 2175.45  4931.8 2173.73
  4938.2 2170.42  4956.1 2167.80  4970.4 2168.07  4994.6 2168.00  5000.0 2167.70
  5000.2 2167.20  5003.7 2167.20  5004.0 2167.70  5012.0 2169.71  5022.0 2173.04
  5032.1 2174.52  5042.1 2177.26  5052.1 2180.34  5062.1 2182.84  5092.2 2183.90
  5098.4 2185.34  5103.4 2184.80  5132.3 2193.92  5140.5 2197.90  5143.7 2197.90
#Mann=4,-1,0
  4857.8    0.07       0  4861.3    0.16       0  5000.0    0.07       0
  5004.0    0.16       0
Bank Sta=5000,5004
Exp/Cntr=0.3,0.1

Type RM Length L Ch R = 1,928,131,131,131
BEGIN DESCRIPTION:
Elm 58 927.663
END DESCRIPTION:
XS GIS Cut Line= 3
      1519605.02      6764887.98      1519701.78      6764779.72
      1519705.00      6764587.95
#Sta/Elev= 30
  4854.8 2194.00  4858.1 2194.00  4861.9 2191.85  4882.8 2185.31  4904.5 2180.67
  4939.6 2175.99  4961.3 2172.17  4968.0 2174.66  4982.3 2168.75  4996.5 2166.66
  4998.7 2165.62  5003.4 2165.62  5009.7 2163.76  5010.0 2163.26  5013.5 2163.26
  5013.7 2163.76  5021.7 2167.68  5031.7 2171.95  5041.7 2172.69  5051.7 2172.87
  5091.7 2176.61  5111.7 2180.92  5121.7 2183.53  5147.5 2191.83  5151.7 2193.33
  5161.7 2195.71  5171.7 2196.08  5181.7 2197.64  5189.3 2199.98  5191.8 2199.98
#Mann=4,-1,0
  4854.8    0.16       0  5009.7    0.07       0  5013.7    0.16       0
  5147.5    0.07       0
Bank Sta=5009.7,5013.7
Exp/Cntr=0.3,0.1

Type RM Length L Ch R = 1,797,128,128,128
BEGIN DESCRIPTION:
Elm 58 796.98
END DESCRIPTION:
XS GIS Cut Line= 3
      1519744.17      6764963.89      1519806.69      6764786.76
      1519886.09      6764686.53
#Sta/Elev= 30
  4808.7 2181.24  4823.2 2180.87  4828.5 2182.23  4836.1 2181.59  4854.2 2177.03
  4868.0 2174.86  4881.5 2174.19  4887.3 2173.83  4921.3 2171.39  4977.9 2170.80
  4984.6 2170.14  4993.2 2167.99  4998.9 2167.99  5001.6 2165.30  5022.4 2163.38
  5034.8 2161.00  5035.1 2160.50  5038.8 2161.00  5042.9 2163.09  5044.9 2164.11
  5051.3 2164.05  5065.7 2174.11  5072.1 2175.24  5080.1 2181.45  5086.5 2184.52
  5094.6 2190.37  5109.0 2196.04  5115.4 2194.84  5120.3 2191.89  5124.4 2191.89
#Mann=6,-1,0
  4808.7    0.16       0  4881.5    0.07       0  4887.3    0.16       0
  5034.8    0.07       0  5038.8    0.16       0  5042.9    0.07       0
Bank Sta=5034.8,5038.8
Exp/Cntr=0.3,0.1

Type RM Length L Ch R = 1,669,85,85,85
BEGIN DESCRIPTION:
Elm 58 668.99
END DESCRIPTION:
XS GIS Cut Line= 3
      1519869.20      6764944.27      1519921.27      6764836.24
      1519986.22      6764742.71
#Sta/Elev= 30
  4879.1 2181.86  4886.3 2181.25  4894.4 2181.59  4908.9 2180.98  4919.4 2177.83
  4926.0 2173.07  4931.5 2171.56  4941.6 2167.73  4948.6 2166.50  4954.1 2166.46
  4971.2 2167.62  4976.7 2164.67  4991.8 2158.61  4992.1 2158.11  4995.6 2158.11
  4995.8 2158.61  4997.6 2159.72  5008.7 2161.35  5026.6 2164.72  5029.6 2165.37
  5035.7 2168.05  5044.4 2170.48  5050.5 2173.41  5071.5 2180.24  5080.2 2181.41
  5086.3 2183.77  5094.3 2183.69  5101.2 2184.29  5107.3 2185.68  5112.9 2187.59
#Mann=5,-1,0
  4879.1    0.07       0  4894.4    0.16       0  4991.8    0.07       0
  4995.8    0.16       0  5026.6    0.07       0
Bank Sta=4991.8,4995.8
Exp/Cntr=0.3,0.1

Type RM Length L Ch R = 1,584,80,80,80
BEGIN DESCRIPTION:
Elm 58 583.52
END DESCRIPTION:
XS GIS Cut Line= 3
      1519891.31      6764975.58      1519990.28      6764879.21
      1520051.41      6764834.63
#Sta/Elev= 30
  4858.8 2181.66  4866.7 2181.78  4880.9 2181.16  4888.0 2180.14  4895.0 2177.76
  4898.9 2176.84  4902.2 2176.06  4909.2 2175.14  4916.3 2172.22  4923.3 2171.97
  4930.5 2169.64  4937.4 2168.13  4944.6 2165.75  4958.8 2164.72  4965.7 2165.31
  4972.9 2164.12  4992.0 2157.51  4992.3 2157.01  4995.8 2157.01  4996.0 2157.51
  4996.7 2158.45  5002.2 2158.45  5015.2 2163.91  5022.9 2168.54  5037.6 2176.67
  5043.8 2179.65  5052.2 2184.53  5058.4 2186.23  5064.7 2189.13  5072.6 2189.93
#Mann=4,-1,0
  4858.8    0.07       0  4898.9    0.16       0  4992.0    0.07       0
  4996.0    0.16       0
Bank Sta=4992,4996
Exp/Cntr=0.3,0.1

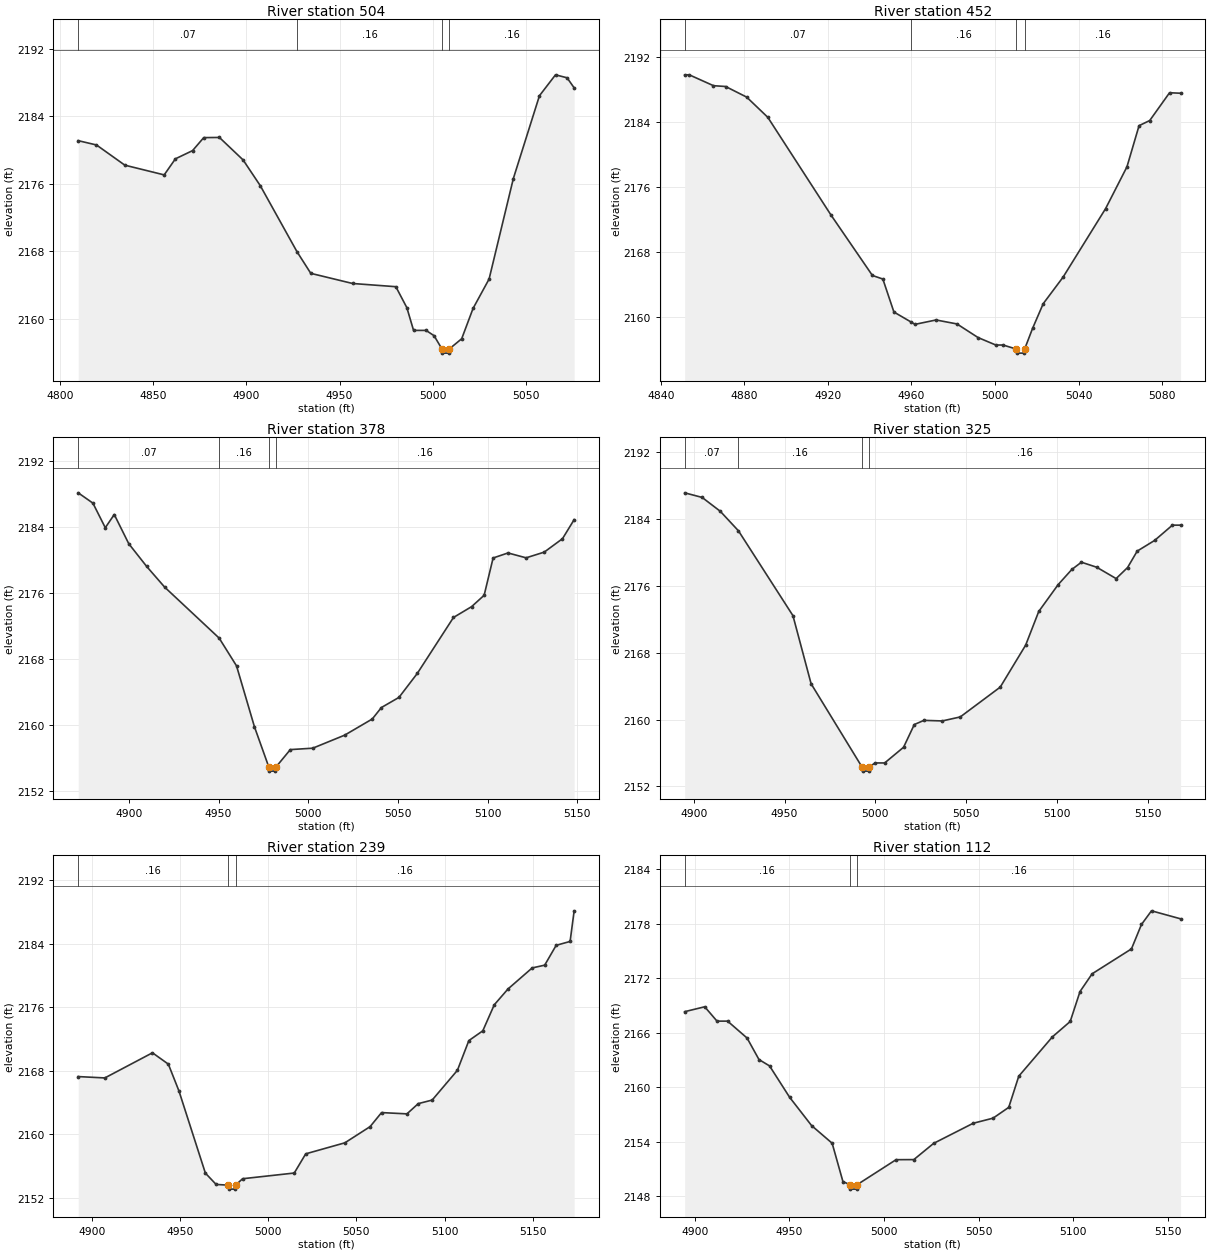
Type RM Length L Ch R = 1,504,52,52,52
BEGIN DESCRIPTION:
Elm 58 504.16
END DESCRIPTION:
XS GIS Cut Line= 3
      1519891.33      6765038.06      1520044.97      6764939.11
      1520093.42      6764871.53
#Sta/Elev= 30
  4809.9 2181.10  4819.7 2180.59  4834.9 2178.20  4856.0 2177.05  4862.0 2178.95
  4871.2 2179.92  4877.2 2181.46  4885.6 2181.48  4898.3 2178.82  4907.5 2175.78
  4927.2 2167.96  4934.6 2165.40  4957.0 2164.20  4980.2 2163.82  4986.1 2161.34
  4989.7 2158.65  4996.4 2158.65  5000.7 2158.02  5004.9 2156.46  5005.1 2155.96
  5008.6 2155.96  5008.9 2156.46  5015.5 2157.66  5021.6 2161.25  5030.2 2164.73
  5043.2 2176.62  5057.2 2186.42  5065.8 2188.89  5072.0 2188.54  5075.8 2187.35
#Mann=4,-1,0
  4809.9    0.07       0  4927.2    0.16       0  5004.9    0.07       0
  5008.9    0.16       0
Bank Sta=5004.9,5008.9
Exp/Cntr=0.3,0.1

Type RM Length L Ch R = 1,452,74,74,74
BEGIN DESCRIPTION:
Elm 58 449.388
END DESCRIPTION:
XS GIS Cut Line= 3
      1520068.41      6765117.46      1520087.08      6764966.06
      1520103.78      6764882.76
#Sta/Elev= 30
  4851.4 2189.85  4853.6 2189.85  4865.2 2188.51  4871.0 2188.41  4881.1 2187.10
  4891.2 2184.61  4921.4 2172.58  4941.3 2165.10  4946.3 2164.66  4951.6 2160.59
  4959.6 2159.39  4961.7 2159.07  4971.8 2159.61  4981.8 2159.12  4991.9 2157.44
  5000.4 2156.52  5003.9 2156.52  5010.2 2156.02  5010.4 2155.52  5013.9 2155.52
  5014.2 2156.02  5018.0 2158.57  5023.1 2161.62  5032.6 2164.89  5053.0 2173.36
  5063.2 2178.50  5069.0 2183.58  5074.1 2184.21  5083.6 2187.64  5088.9 2187.58
#Mann=4,-1,0
  4851.4    0.07       0  4959.6    0.16       0  5010.2    0.07       0
  5014.2    0.16       0
Bank Sta=5010.2,5014.2
Exp/Cntr=0.3,0.1

Type RM Length L Ch R = 1,378,53,53,53
BEGIN DESCRIPTION:
Elm 58 4813
END DESCRIPTION:
XS GIS Cut Line= 3
      1520149.14      6765116.15      1520155.64      6764988.01
      1520132.43      6764841.54
#Sta/Elev= 30
  4871.7 2188.20  4879.9 2186.95  4886.8 2183.97  4891.8 2185.57  4899.9 2182.03
  4909.9 2179.27  4919.9 2176.77  4950.3 2170.59  4960.0 2167.22  4970.0 2159.83
  4978.0 2154.96  4978.2 2154.46  4981.7 2154.46  4982.0 2154.96  4990.0 2157.07
  5002.5 2157.24  5020.3 2158.82  5035.7 2160.78  5040.8 2162.17  5050.6 2163.40
  5060.8 2166.30  5081.0 2173.09  5091.1 2174.40  5098.1 2175.78  5103.1 2180.30
  5111.4 2180.91  5121.5 2180.32  5131.6 2181.01  5141.8 2182.64  5148.3 2184.95
#Mann=4,-1,0
  4871.7    0.07       0  4950.3    0.16       0  4978.0    0.07       0
  4982.0    0.16       0
Bank Sta=4978,4982
Exp/Cntr=0.3,0.1

Type RM Length L Ch R = 1,325,86,86,86
BEGIN DESCRIPTION:
Elm 58 4812
END DESCRIPTION:
XS GIS Cut Line= 3
      1520205.12      6765087.58      1520207.43      6764982.60
      1520150.45      6764824.56
#Sta/Elev= 30
  4895.0 2187.17  4904.6 2186.62  4914.6 2184.96  4924.6 2182.62  4954.6 2172.46
  4964.6 2164.30  4992.6 2154.34  4992.9 2153.84  4996.4 2153.84  4996.6 2154.34
  4999.8 2154.82  5005.1 2154.82  5015.5 2156.70  5021.4 2159.42  5026.7 2159.92
  5036.8 2159.85  5046.7 2160.33  5068.7 2163.90  5082.7 2168.93  5089.9 2172.96
  5100.6 2176.18  5108.1 2177.99  5113.4 2178.86  5121.8 2178.26  5132.5 2176.90
  5138.8 2178.22  5144.1 2180.19  5153.7 2181.47  5163.5 2183.30  5168.0 2183.30
#Mann=4,-1,0
  4895.0    0.07       0  4924.6    0.16       0  4992.6    0.07       0
  4996.6    0.16       0
Bank Sta=4992.6,4996.6
Exp/Cntr=0.3,0.1

Type RM Length L Ch R = 1,239,127,127,127
BEGIN DESCRIPTION:
Elm 58 4811
END DESCRIPTION:
XS GIS Cut Line= 3
      1520330.03      6765013.04      1520270.22      6764923.47
      1520159.79      6764789.66
#Sta/Elev= 30
  4892.3 2167.27  4907.4 2167.10  4934.4 2170.27  4943.4 2168.84  4949.4 2165.47
  4964.4 2155.10  4970.5 2153.67  4977.5 2153.58  4977.7 2153.08  4981.2 2153.08
  4981.5 2153.58  4985.5 2154.39  5014.8 2155.11  5021.3 2157.53  5043.5 2158.92
  5057.8 2160.96  5064.3 2162.73  5078.7 2162.57  5085.1 2163.86  5093.0 2164.31
  5107.3 2168.06  5113.8 2171.81  5121.7 2173.04  5128.2 2176.32  5136.0 2178.32
  5149.7 2180.97  5156.8 2181.32  5163.3 2183.82  5171.2 2184.31  5173.5 2188.17
#Mann=3,-1,0
  4892.3    0.16       0  4977.5    0.07       0  4981.5    0.16       0
Bank Sta=4977.5,4981.5
Exp/Cntr=0.3,0.1

Type RM Length L Ch R = 1,112,0,0,0
BEGIN DESCRIPTION:
Elm 58 4810
END DESCRIPTION:
XS GIS Cut Line= 3
      1520408.25      6764927.39      1520360.08      6764833.64
      1520210.34      6764786.77
#Sta/Elev= 30
  4894.6 2168.30  4905.2 2168.84  4911.7 2167.26  4917.3 2167.26  4927.6 2165.40
  4933.9 2163.03  4939.5 2162.33  4950.1 2158.88  4961.7 2155.77  4972.6 2153.82
  4978.3 2149.60  4981.9 2149.27  4982.1 2148.77  4985.6 2148.77  4985.9 2149.27
  5006.4 2152.01  5015.8 2152.02  5026.3 2153.81  5047.2 2156.02  5057.7 2156.58
  5066.0 2157.77  5071.3 2161.20  5089.1 2165.53  5098.5 2167.22  5103.7 2170.52
  5110.1 2172.47  5130.9 2175.21  5136.2 2177.90  5141.5 2179.40  5156.9 2178.52
#Mann=3,-1,0
  4894.6    0.16       0  4981.9    0.07       0  4985.9    0.16       0
Bank Sta=4981.9,4985.9
Exp/Cntr=0.3,0.1

Chan Stop Cuts=-1