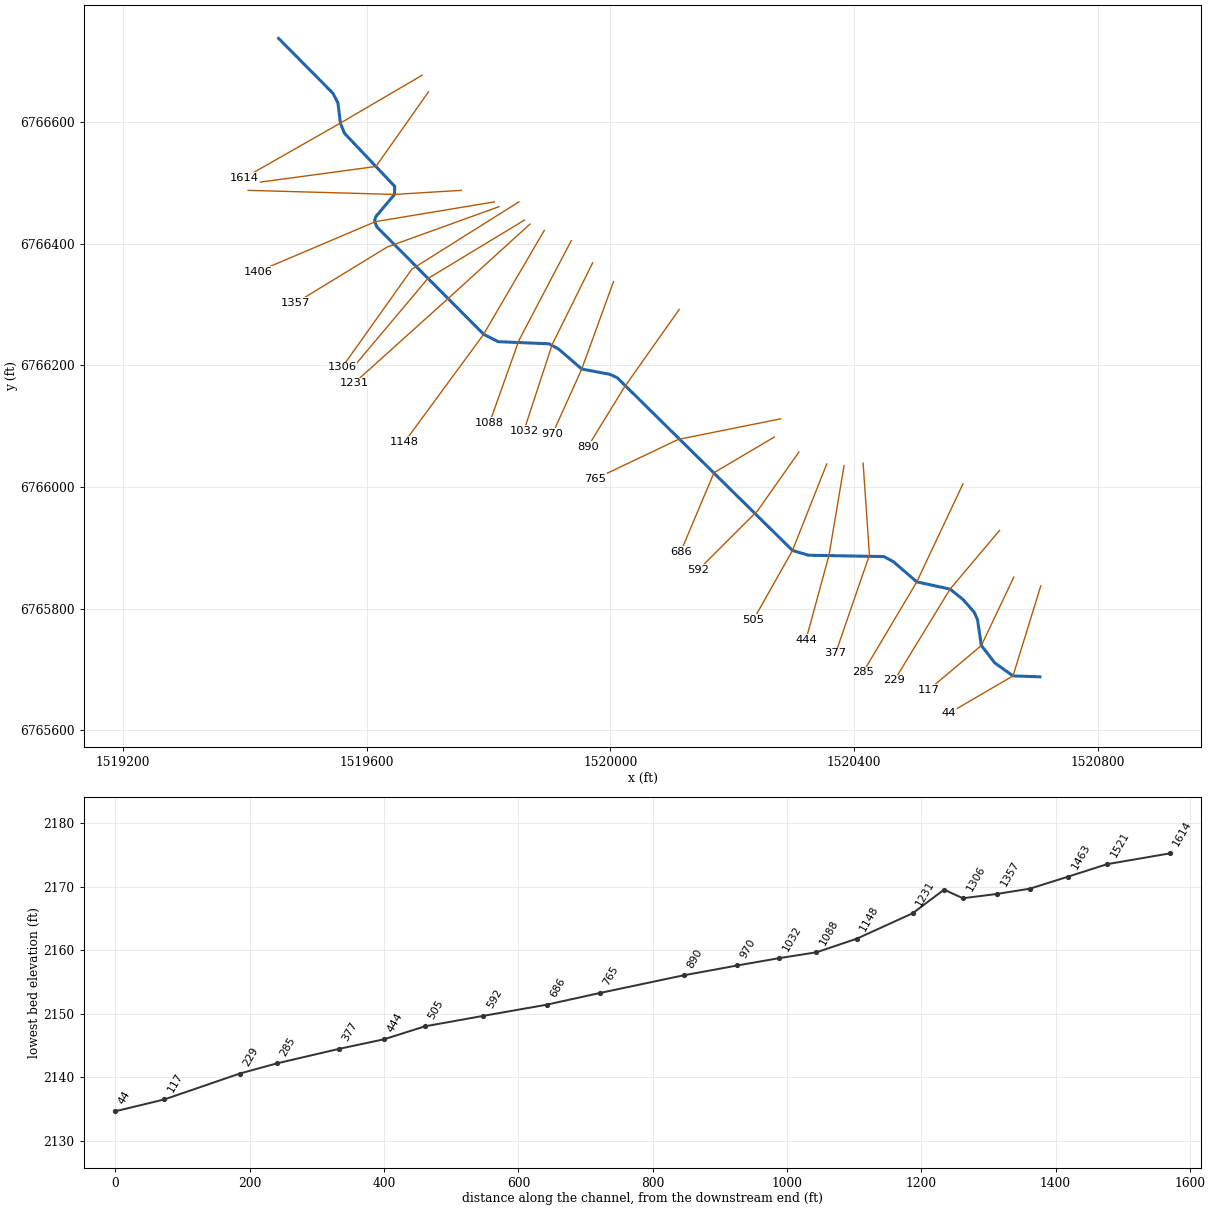
--- Elm 59.prj (project) ---

Proj Title=Elm 59 Base Level Engineering
Current Plan=p01
Default Exp/Contr=0.3,0.1
English Units
Geom File=g01
Flow File=f01
Plan File=p01
Y Axis Title=Elevation
X Axis Title(PF)=Main Channel Distance
X Axis Title(XS)=Station
BEGIN DESCRIPTION:
Elm 59
END DESCRIPTION:
DSS Export Rating Curves= 0
DSS Export Rating Curve Sorted= 0
DSS Export Volume Flow Curves= 0
DXF OffsetX= 0
DXF OffsetY= 0
DXF ScaleX= 1
DXF ScaleY= 10

--- Elm 59.p01 (plan) ---

Plan Title=Multiple Run
Short Identifier=Multiple
Geom File=g01
Flow File=f01
Subcritical Flow
K Sum by GR= 0
Std Step Tol= 0.01
Critical Tol= 0.01
Num of Std Step Trials= 20
Max Error Tol= 0.3
Flow Tol Ratio= 0.001
Split Flow NTrial= 30
Split Flow Tol= 0.02
Split Flow Ratio= 0.02
Log Output Level= 0
Friction Slope Method= 1
Unsteady Friction Slope Method= 2
Unsteady Bridges Friction Slope Method= 1
Parabolic Critical Depth
Global Vel Dist=  1 , 1 , 1
Global Log Level= 0
CheckData=True
Encroach Param= -1, 0, 0, 0
BEGIN DESCRIPTION:
Multiple Run
END DESCRIPTION:

--- Elm 59.f01 (steady flow) ---

Flow Title=Multiple
Number of Profiles=7
Profile Names=10-year,25-year,50-year,1pct_min,100-year,1pct_plu,500-year
River Rch & RM= Elm 59,Reach-1,1614
     130     177     214     163     261     359     389
Boundary for River Rch & Prof#=Elm 59,Reach-1,1
Up Type=0
Dn Type=3
Dn Slope=0.005
Boundary for River Rch & Prof#=Elm 59,Reach-1,2
Up Type=0
Dn Type=3
Dn Slope=0.005
Boundary for River Rch & Prof#=Elm 59,Reach-1,3
Up Type=0
Dn Type=3
Dn Slope=0.005
Boundary for River Rch & Prof#=Elm 59,Reach-1,4
Up Type=0
Dn Type=3
Dn Slope=0.005
Boundary for River Rch & Prof#=Elm 59,Reach-1,5
Up Type=0
Dn Type=3
Dn Slope=0.005
Boundary for River Rch & Prof#=Elm 59,Reach-1,6
Up Type=0
Dn Type=3
Dn Slope=0.005
Boundary for River Rch & Prof#=Elm 59,Reach-1,7
Up Type=0
Dn Type=3
Dn Slope=0.005

--- Elm 59.g01 (geometry) ---

Geom Title=Existing Conditions
Program Version=4.10

River Reach=Elm 59          ,Reach-1
Reach XY= 30
        1519455.        6766738.      1519544.28       6766647.7
      1519552.48      6766631.96      1519556.55      6766598.63
      1519563.19      6766581.95      1519645.68      6766494.66
      1519645.38      6766481.33      1519614.62      6766444.67
      1519612.56        6766438.      1519616.24        6766428.
       1519791.7       6766251.4      1519815.48      6766239.16
      1519899.03      6766235.67      1519914.65      6766227.16
      1519952.83      6766194.14      1519998.97       6766185.5
      1520011.06      6766179.86      1520298.81      6765895.82
      1520324.99      6765887.98      1520449.07      6765885.75
      1520464.67       6765877.2      1520502.85      6765844.15
      1520557.55      6765832.27      1520578.84      6765815.14
      1520596.97      6765794.33      1520602.56      6765782.12
      1520608.87       6765739.5      1520631.02      6765710.83
      1520660.87      6765689.56        1520705.        6765688.

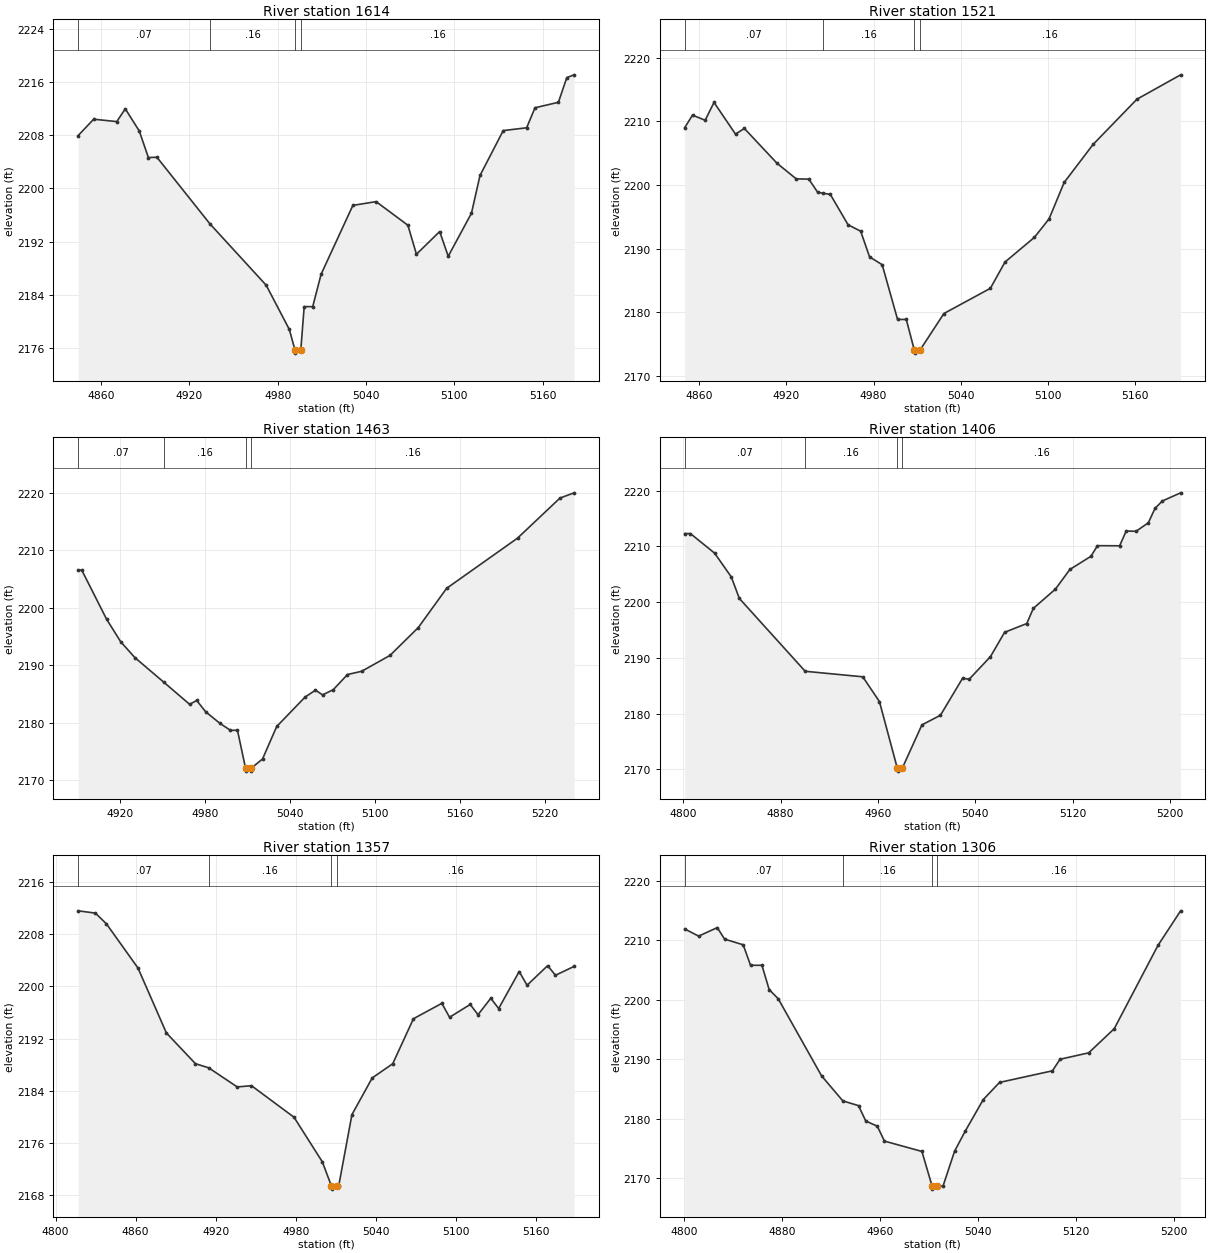
Type RM Length L Ch R = 1 ,1614    ,93,93,93
BEGIN DESCRIPTION:
Elm 59 4858
END DESCRIPTION:
XS GIS Cut Line= 3
      1519690.76      6766677.36      1519556.55      6766598.63
      1519398.88      6766508.72
#Sta/Elev= 30
  4844.4 2207.94  4854.9 2210.39  4870.6 2210.03  4876.4 2211.95  4885.9 2208.62
  4892.1 2204.63  4897.9 2204.67  4933.9 2194.67  4972.2 2185.43  4987.9 2178.79
  4991.7 2175.73  4991.9 2175.23  4995.7 2175.73    4998 2182.22  5003.8 2182.22
  5009.5 2187.09  5031.1 2197.44  5046.9    2198  5068.5 2194.45  5074.3 2190.09
  5090.1 2193.51  5095.9 2189.79  5111.7 2196.26  5117.5 2201.93  5133.3 2208.68
  5149.2  2209.1  5154.9 2212.11  5170.8 2212.93  5176.5 2216.64  5181.5 2217.06
#Mann= 4 ,-1 , 0
  4844.4     .07       0  4933.9     .16       0  4991.7     .07       0
  4995.7     .16       0
Bank Sta=4991.7,4995.7
XS Rating Curve= 0 ,0
Exp/Cntr=0.3,0.1

Type RM Length L Ch R = 1 ,1521    ,58,58,58
BEGIN DESCRIPTION:
Elm 59 4859
END DESCRIPTION:
XS GIS Cut Line= 3
      1519701.21      6766650.04      1519614.87      6766527.26
       1519425.2      6766501.61
#Sta/Elev= 30
  4849.9 2209.01  4855.3 2210.99    4864 2210.18  4870.1 2212.99  4884.9    2208
    4891 2208.89  4913.5 2203.41  4926.7 2200.96  4935.4 2200.92  4941.5 2198.84
  4945.3  2198.7  4950.2 2198.51  4962.4 2193.74  4971.1 2192.72  4977.2 2188.69
  4985.9 2187.45  4996.5 2178.84  5002.5 2178.84    5008 2174.04  5008.2 2173.54
    5012 2174.04  5028.4 2179.77  5060.4 2183.74  5070.5 2187.88  5090.7 2191.75
  5100.8 2194.66  5111.2 2200.39  5131.1 2206.37  5161.3 2213.49  5191.4 2217.33
#Mann= 4 ,-1 , 0
  4849.9     .07       0  4945.3     .16       0    5008     .07       0
    5012     .16       0
Bank Sta=5008,5012
XS Rating Curve= 0 ,0
Exp/Cntr=0.3,0.1

Type RM Length L Ch R = 1 ,1463    ,57,57,57
BEGIN DESCRIPTION:
Elm 59 1462.9
END DESCRIPTION:
XS GIS Cut Line= 3
      1519754.97        6766488.      1519645.38      6766481.33
      1519404.97        6766488.
#Sta/Elev= 30
  4890.2 2206.58  4892.7 2206.58  4910.2 2198.05  4920.2 2194.11  4930.2 2191.35
  4950.9 2187.01  4968.9 2183.21  4973.9 2183.88  4980.3 2181.89  4990.4 2179.88
  4997.7 2178.69  5002.7 2178.69  5008.4 2172.08  5008.6 2171.58  5012.1 2171.58
  5012.4 2172.08  5020.4  2173.7  5030.4 2179.35  5050.4 2184.46  5057.8 2185.68
  5062.8 2184.85  5070.4 2185.77  5080.4  2188.4  5090.4 2188.96  5110.4 2191.72
  5130.4 2196.57  5150.4  2203.4  5200.5 2212.14  5230.5 2219.12  5240.5 2220.03
#Mann= 4 ,-1 , 0
  4890.2     .07       0  4950.9     .16       0  5008.4     .07       0
  5012.4     .16       0
Bank Sta=5008.4,5012.4
XS Rating Curve= 0 ,0
Exp/Cntr=0.3,0.1

Type RM Length L Ch R = 1 ,1406    ,49,49,49
BEGIN DESCRIPTION:
Elm 59 1406.13
END DESCRIPTION:
XS GIS Cut Line= 3
      1519809.27      6766469.05      1519613.98       6766436.5
       1519421.3      6766354.48
#Sta/Elev= 30
  4801.2 2212.29  4805.9 2212.29  4825.8 2208.78  4839.5 2204.51  4846.1 2200.66
  4900.2 2187.59  4947.5  2186.6  4961.2 2182.15  4975.9 2170.18  4976.1 2169.68
  4979.9 2170.18  4996.1 2177.98  5011.3  2179.7  5029.5 2186.34  5034.9 2186.16
  5052.4 2190.22    5064 2194.58  5082.2 2196.15  5087.6 2198.87  5105.8 2202.34
  5117.6 2205.85  5134.9 2208.21  5140.3 2210.12  5158.5  2210.1  5163.9 2212.75
    5172  2212.7  5182.1 2214.23  5187.6 2216.83  5193.7 2218.15  5208.6  2219.6
#Mann= 4 ,-1 , 0
  4801.2     .07       0  4900.2     .16       0  4975.9     .07       0
  4979.9     .16       0
Bank Sta=4975.9,4979.9
XS Rating Curve= 0 ,0
Exp/Cntr=0.3,0.1

Type RM Length L Ch R = 1 ,1357    ,51,51,51
BEGIN DESCRIPTION:
Elm 59 1356.54
END DESCRIPTION:
XS GIS Cut Line= 3
      1519817.14      6766461.25      1519633.51      6766394.83
      1519482.94      6766302.68
#Sta/Elev= 30
    4817 2211.63  4829.9 2211.28  4838.2 2209.62  4861.8 2202.84  4883.1 2192.86
  4904.9 2188.13  4914.8  2187.5  4936.2 2184.56  4946.9 2184.75  4978.8  2179.9
    5000 2173.05  5006.8 2169.35  5007.1 2168.85  5010.8 2169.35  5012.3 2169.35
  5022.2  2180.3  5037.4 2185.94  5052.8 2188.13  5068.3 2195.04  5089.6 2197.41
  5095.4 2195.27  5110.9 2197.24  5116.7 2195.66  5126.3 2198.19  5132.2 2196.61
  5147.6  2202.3  5153.5 2200.19  5168.9  2203.2  5174.8 2201.73  5188.8 2203.09
#Mann= 4 ,-1 , 0
    4817     .07       0  4914.8     .16       0  5006.8     .07       0
  5010.8     .16       0
Bank Sta=5006.8,5010.8
XS Rating Curve= 0 ,0
Exp/Cntr=0.3,0.1

Type RM Length L Ch R = 1 ,1306    ,28,28,28
BEGIN DESCRIPTION:
Elm 59 1305.57
END DESCRIPTION:
XS GIS Cut Line= 3
      1519849.63      6766469.04      1519673.87      6766358.38
      1519559.62      6766197.39
#Sta/Elev= 30
  4800.7 2211.89  4812.1 2210.68  4827.3 2212.11  4833.3 2210.18  4848.5 2209.22
  4854.5 2205.78  4863.8 2205.78  4869.7  2201.7  4877.1 2200.16  4912.5 2187.21
  4929.9 2182.99  4942.7  2182.2  4948.6 2179.62    4958 2178.75  4963.9 2176.24
  4994.5  2174.5  5002.8 2168.67    5003 2168.17  5006.8 2168.67  5011.7 2168.67
  5021.2 2174.56  5029.8 2177.89  5044.6 2183.22  5057.9  2186.1  5101.1 2188.05
  5107.3 2189.99  5130.7 2191.07  5151.6 2195.13  5187.3 2209.12  5205.8 2214.93
#Mann= 4 ,-1 , 0
  4800.7     .07       0  4929.9     .16       0  5002.8     .07       0
  5006.8     .16       0
Bank Sta=5002.8,5006.8
XS Rating Curve= 0 ,0
Exp/Cntr=0.3,0.1

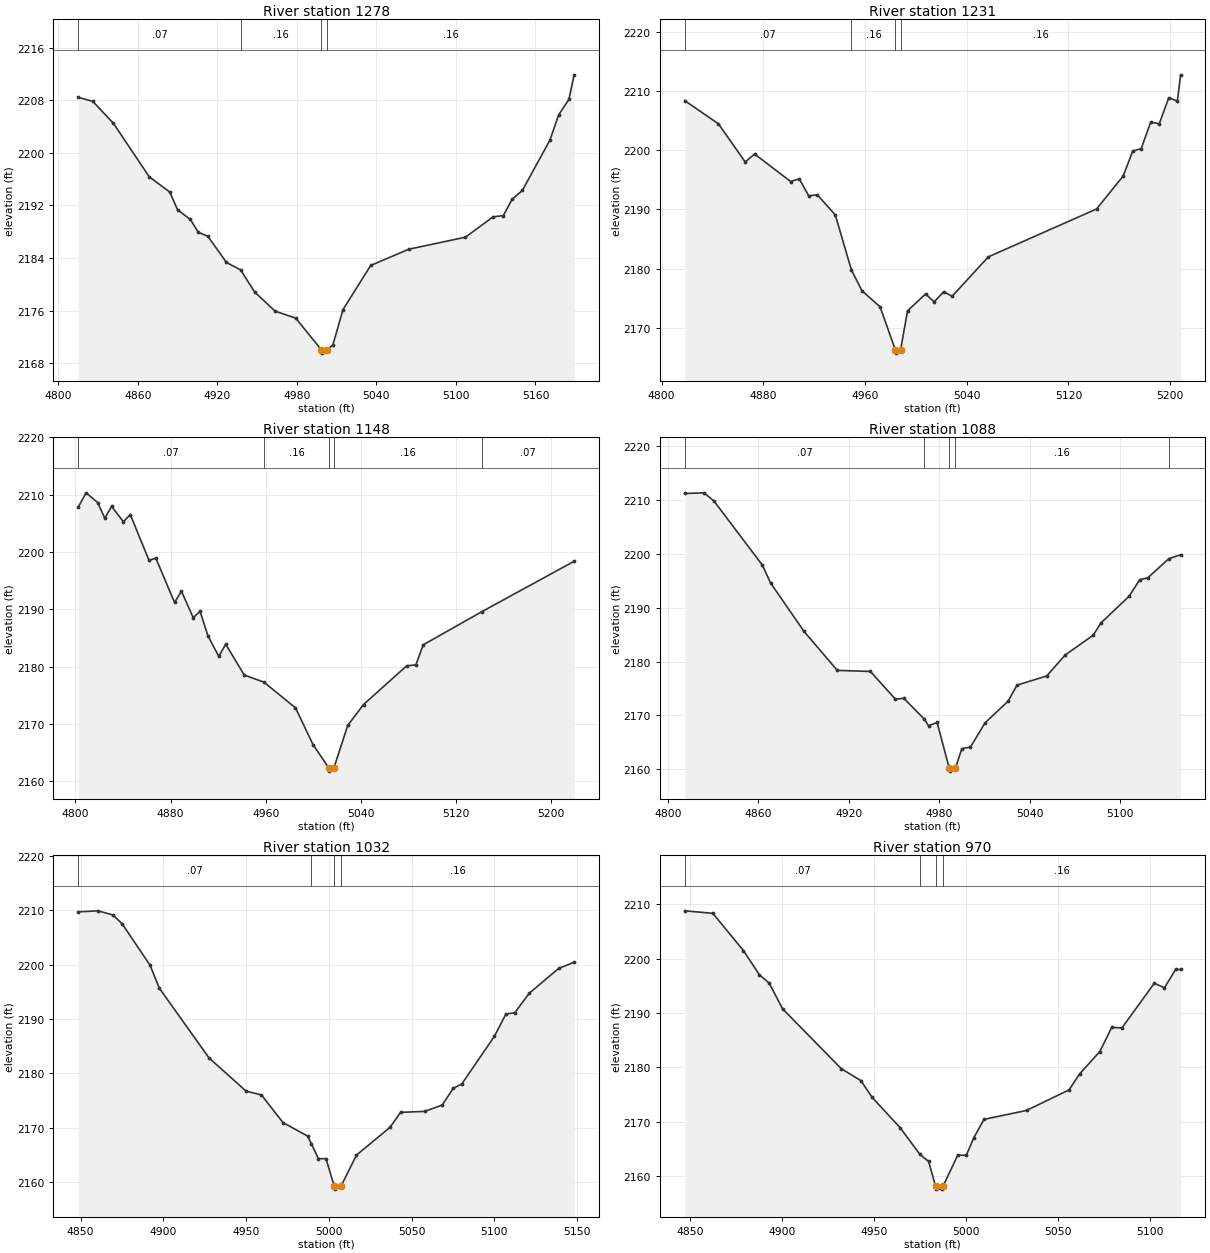
Type RM Length L Ch R = 1 ,1278    ,47,47,47
BEGIN DESCRIPTION:
Elm 59 1277.79
END DESCRIPTION:
XS GIS Cut Line= 3
      1519858.73      6766439.08      1519699.91      6766342.75
      1519578.76       6766198.4
#Sta/Elev= 30
    4815 2208.44    4826 2207.82  4841.5  2204.5  4868.6 2196.35  4884.1 2194.02
    4890 2191.31  4899.6 2189.86  4905.5 2187.93  4912.9 2187.28  4926.8 2183.33
  4937.6 2182.17  4948.1 2178.82  4963.6  2175.9  4979.1 2174.85  4998.5 2170.02
  4998.7 2169.52  5002.5 2170.02  5007.1 2170.73  5014.8 2176.15  5035.7 2182.86
  5064.3 2185.32  5107.2 2187.16    5128 2190.25  5135.8 2190.45  5142.3  2192.9
  5150.1 2194.27  5170.9 2201.92  5177.5 2205.76  5185.2 2208.11  5189.2 2211.86
#Mann= 4 ,-1 , 0
    4815     .07       0  4937.6     .16       0  4998.5     .07       0
  5002.5     .16       0
Bank Sta=4998.5,5002.5
XS Rating Curve= 0 ,0
Exp/Cntr=0.3,0.1

Type RM Length L Ch R = 1 ,1231    ,83,83,83
BEGIN DESCRIPTION:
Elm 59 1231.22
END DESCRIPTION:
XS GIS Cut Line= 3
      1519867.87      6766432.58      1519736.37       6766312.8
      1519578.75      6766170.68
#Sta/Elev= 30
  4818.1 2208.36  4844.7 2204.43  4865.7 2198.01  4873.1 2199.35  4901.5 2194.71
  4908.2 2195.18  4915.7  2192.3  4922.4 2192.49  4936.6 2189.07  4949.2 2179.84
  4957.6 2176.29  4971.8 2173.59  4983.9 2166.29  4984.2 2165.79  4987.9 2166.29
  4993.4 2172.92  5007.6 2175.77  5014.3 2174.44  5021.8 2176.14  5028.5 2175.38
  5056.9 2182.01  5142.1 2190.09    5163 2195.63  5170.5 2199.84  5177.2 2200.27
  5184.7 2204.74  5191.4 2204.45  5198.9 2208.84  5205.6 2208.26  5208.2  2212.7
#Mann= 4 ,-1 , 0
  4818.1     .07       0  4949.2     .16       0  4983.9     .07       0
  4987.9     .16       0
Bank Sta=4983.9,4987.9
XS Rating Curve= 0 ,0
Exp/Cntr=0.3,0.1

Type RM Length L Ch R = 1 ,1148    ,60,60,60
BEGIN DESCRIPTION:
Elm 59 1148.47
END DESCRIPTION:
XS GIS Cut Line= 3
      1519891.32      6766422.17      1519791.06       6766250.3
      1519662.13      6766074.48
#Sta/Elev= 30
  4802.3 2207.82  4808.9 2210.31  4818.7 2208.62  4824.6  2205.9  4830.4 2207.94
  4840.3 2205.27  4846.1 2206.52  4861.8 2198.55  4867.6 2198.92  4883.3  2191.2
  4889.1 2193.16    4899 2188.55  4904.8 2189.65  4911.3 2185.42  4920.5  2181.8
  4926.3 2183.92    4942 2178.53  4958.4 2177.32    4985 2172.83  4999.7 2166.44
  5013.2  2162.3  5013.4  2161.8  5017.2  2162.3  5028.9 2169.76  5042.2 2173.41
  5078.5 2180.16  5086.2 2180.32  5092.4 2183.82  5141.9 2189.62  5219.3 2198.38
#Mann= 5 ,-1 , 0
  4802.3     .07       0  4958.4     .16       0  5013.2     .07       0
  5017.2     .16       0  5141.9     .07       0
Bank Sta=5013.2,5017.2
XS Rating Curve= 0 ,0
Exp/Cntr=0.3,0.1

Type RM Length L Ch R = 1 ,1088    ,56,56,56
BEGIN DESCRIPTION:
Elm 59 1088.43
END DESCRIPTION:
XS GIS Cut Line= 3
      1519935.58      6766405.23      1519849.65      6766241.19
      1519801.48      6766105.79
#Sta/Elev= 30
  4811.2 2211.25  4824.1 2211.37  4830.7 2209.82  4862.6 2197.99  4868.2 2194.61
  4890.3 2185.64  4912.4 2178.38  4934.4 2178.18  4950.9 2173.04  4956.5 2173.19
  4970.2 2169.31  4972.9 2168.08  4978.6  2168.7  4986.7 2160.16  4986.9 2159.66
  4990.7 2160.16    4995 2163.84  5000.7 2164.13  5010.4 2168.63  5025.7 2172.66
  5031.6 2175.64  5051.3 2177.34  5063.5 2181.23  5082.1 2184.91  5087.4 2187.23
  5105.9 2192.14    5113 2195.24  5118.3 2195.57  5132.3 2199.14  5140.1 2199.87
#Mann= 5 ,-1 , 0
  4811.2     .07       0  4970.2     .16       0  4986.7     .07       0
  4990.7     .16       0  5132.3     .07       0
Bank Sta=4986.7,4990.7
XS Rating Curve= 0 ,0
Exp/Cntr=0.3,0.1

Type RM Length L Ch R = 1 ,1032    ,62,62,62
BEGIN DESCRIPTION:
Elm 59 1032.35
END DESCRIPTION:
XS GIS Cut Line= 3
      1519970.77      6766368.84      1519904.34      6766234.68
      1519857.72      6766092.22
#Sta/Elev= 30
  4848.6  2209.7  4860.7 2209.89  4869.6 2209.12  4875.1 2207.53    4892 2199.89
  4897.6 2195.67  4927.6 2182.86    4950 2176.75  4959.3 2176.04  4972.3 2170.97
  4987.3 2168.46  4989.4  2167.1  4993.7 2164.33  4998.3 2164.33  5003.3 2159.23
  5003.6 2158.73  5007.3 2159.23  5016.7 2164.99  5036.9 2170.07  5043.3 2172.84
  5057.9 2173.02  5068.5 2174.19  5075.1 2177.23  5080.4  2178.1    5100 2186.81
    5107 2190.93  5112.3 2191.14  5121.1 2194.75  5138.9 2199.32  5148.2 2200.43
#Mann= 4 ,-1 , 0
  4848.6     .07       0  4989.4     .16       0  5003.3     .07       0
  5007.3     .16       0
Bank Sta=5003.3,5007.3
XS Rating Curve= 0 ,0
Exp/Cntr=0.3,0.1

Type RM Length L Ch R = 1 ,970     ,80,80,80
BEGIN DESCRIPTION:
Elm 59 969.528
END DESCRIPTION:
XS GIS Cut Line= 3
      1520004.99      6766337.97      1519952.83      6766194.14
      1519905.01      6766088.02
#Sta/Elev= 30
    4847  2208.8  4862.3 2208.34  4878.9 2201.49  4887.6 2197.03  4892.9  2195.5
  4900.2 2190.76  4932.1 2179.74  4942.7 2177.56  4948.8 2174.48    4964  2168.9
  4974.8 2163.97  4979.5 2162.67  4983.3 2158.08  4983.5 2157.58    4987 2157.58
  4987.3 2158.08  4995.3 2163.82    5000 2163.82  5004.1 2167.06  5009.6 2170.42
  5032.7 2172.06  5055.8 2175.85  5061.6 2178.81  5072.5  2182.9    5079 2187.36
  5084.5 2187.24  5102.1 2195.47  5107.6 2194.63  5113.7 2198.01  5116.4 2198.01
#Mann= 4 ,-1 , 0
    4847     .07       0  4974.8     .16       0  4983.3     .07       0
  4987.3     .16       0
Bank Sta=4983.3,4987.3
XS Rating Curve= 0 ,0
Exp/Cntr=0.3,0.1

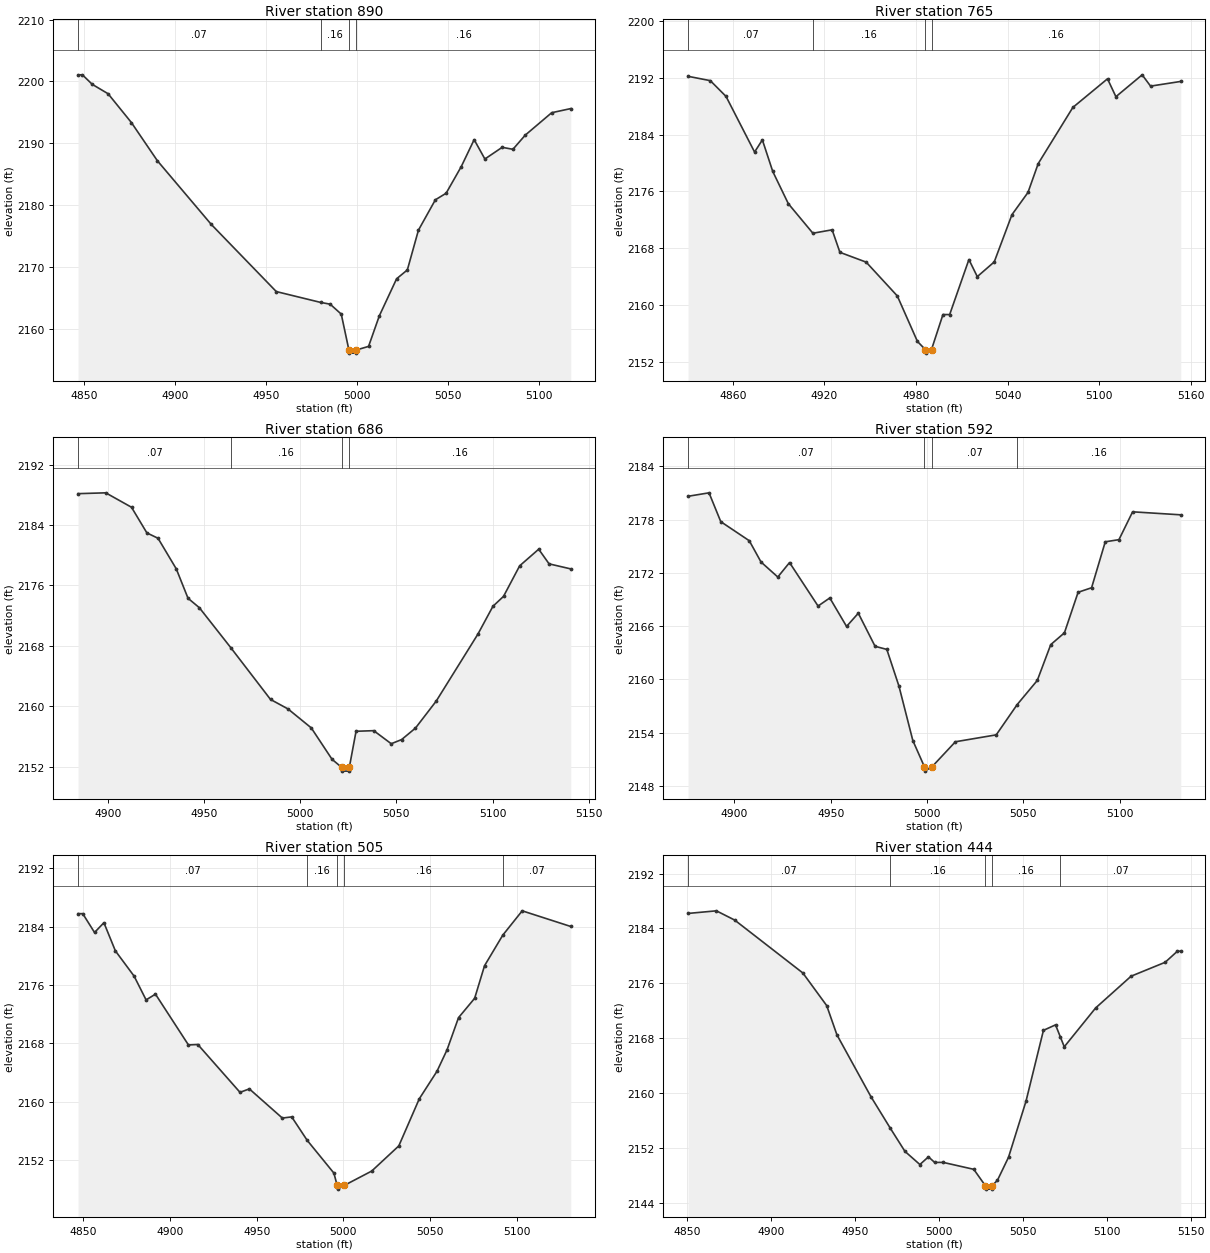
Type RM Length L Ch R = 1 ,890     ,125,125,125
BEGIN DESCRIPTION:
Elm 59 890.44
END DESCRIPTION:
XS GIS Cut Line= 3
      1520112.69        6766292.      1520022.83      6766164.37
      1519962.91      6766066.67
#Sta/Elev= 30
  4846.7 2201.06  4849.1 2201.06  4854.5 2199.52  4863.2    2198    4876 2193.34
  4890.3 2187.15  4919.9 2176.85  4955.6 2165.99  4979.9 2164.24  4985.2 2163.95
  4991.3 2162.34  4995.5 2156.53  4995.8 2156.03  4999.3 2156.03  4999.5 2156.53
  5006.3 2157.12  5012.2 2162.06  5021.7 2168.06  5027.6 2169.49  5033.7 2175.93
    5043 2180.84  5048.9  2181.9  5057.2  2186.2  5064.3 2190.57  5070.2 2187.44
  5079.7 2189.33  5085.6 2189.01  5092.4 2191.31  5106.9 2194.93  5117.4  2195.6
#Mann= 4 ,-1 , 0
  4846.7     .07       0  4979.9     .16       0  4995.5     .07       0
  4999.5     .16       0
Bank Sta=4995.5,4999.5
XS Rating Curve= 0 ,0
Exp/Cntr=0.3,0.1

Type RM Length L Ch R = 1 ,765     ,79,79,79
BEGIN DESCRIPTION:
Elm 59 765.44
END DESCRIPTION:
XS GIS Cut Line= 3
      1520279.36      6766112.29      1520111.37      6766078.43
      1519974.65      6766013.32
#Sta/Elev= 30
  4830.7 2192.21  4845.3  2191.6  4855.6 2189.38  4874.3 2181.55  4879.4 2183.26
  4886.2 2178.82  4896.4 2174.28  4912.5 2170.12  4925.1  2170.6  4930.2 2167.43
  4947.4 2166.05  4967.8 2161.29    4981 2154.88  4986.2 2153.74  4986.4 2153.24
  4990.2 2153.74  4997.7 2158.67  5002.1 2158.67  5014.7 2166.41  5020.2 2164.01
  5031.3 2166.08  5042.9 2172.73  5053.4 2175.86  5060.1 2179.92  5082.8 2187.83
  5105.5 2191.86    5111 2189.34  5128.2 2192.42  5133.7 2190.83  5153.5 2191.49
#Mann= 4 ,-1 , 0
  4830.7     .07       0  4912.5     .16       0  4986.2     .07       0
  4990.2     .16       0
Bank Sta=4986.2,4990.2
XS Rating Curve= 0 ,0
Exp/Cntr=0.3,0.1

Type RM Length L Ch R = 1 ,686     ,94,94,94
BEGIN DESCRIPTION:
Elm 59 686.27
END DESCRIPTION:
XS GIS Cut Line= 3
      1520268.95      6766082.35      1520169.97      6766023.74
      1520115.26      6765893.49
#Sta/Elev= 30
  4884.4 2188.16  4898.8 2188.27  4912.2 2186.36  4920.2 2182.96    4926 2182.25
  4935.5 2178.19  4941.6  2174.3  4947.5 2173.05  4963.8 2167.77  4984.5  2160.9
  4993.6 2159.64  5005.7 2157.13  5016.5 2152.97  5021.5  2151.9  5021.8  2151.4
  5025.3  2151.4  5025.5  2151.9    5029 2156.68  5038.2 2156.76  5047.3 2155.03
  5052.7 2155.58  5059.9  2157.1  5070.7 2160.68  5092.4 2169.56  5100.2 2173.24
  5105.7 2174.55  5114.1  2178.6    5124  2180.8  5129.4 2178.86  5140.7 2178.19
#Mann= 4 ,-1 , 0
  4884.4     .07       0  4963.8     .16       0  5021.5     .07       0
  5025.5     .16       0
Bank Sta=5021.5,5025.5
XS Rating Curve= 0 ,0
Exp/Cntr=0.3,0.1

Type RM Length L Ch R = 1 ,592     ,87,87,87
BEGIN DESCRIPTION:
Elm 59 591.65
END DESCRIPTION:
XS GIS Cut Line= 3
      1520309.28      6766057.58      1520241.58      6765961.24
      1520143.96      6765863.62
#Sta/Elev= 30
  4875.9 2180.63  4886.8 2181.02  4892.9 2177.77  4907.7 2175.62  4913.8 2173.22
  4922.5 2171.53  4928.6 2173.16  4943.4 2168.26  4949.5 2169.17  4958.2 2165.96
  4964.3 2167.45    4973 2163.72  4979.1 2163.37  4985.4 2159.23  4992.6  2153.1
  4998.6 2150.15  4998.8 2149.65  5002.6 2150.15  5014.7 2152.96  5035.9 2153.74
  5046.8 2157.16  5057.2 2159.87  5064.2 2163.91  5071.3 2165.24  5078.4 2169.81
  5085.4 2170.32  5092.5  2175.5  5099.6 2175.74  5106.7 2178.88  5131.7 2178.54
#Mann= 4 ,-1 , 0
  4875.9     .07       0  4998.6     .07       0  5002.6     .07       0
  5046.8     .16       0
Bank Sta=4998.6,5002.6
XS Rating Curve= 0 ,0
Exp/Cntr=0.3,0.1

Type RM Length L Ch R = 1 ,505     ,61,61,61
BEGIN DESCRIPTION:
Elm 59 504.916
END DESCRIPTION:
XS GIS Cut Line= 3
      1520355.01      6766038.01      1520298.81      6765895.82
      1520234.56      6765781.65
#Sta/Elev= 30
  4847.1 2185.79  4849.8 2185.79  4856.6 2183.21    4862 2184.55  4868.6 2180.69
  4879.4 2177.22  4886.3 2173.96  4891.7 2174.75  4910.7 2167.78  4916.1 2167.84
  4940.4 2161.28  4945.8 2161.75  4964.8 2157.75  4970.2 2157.91  4979.1  2154.7
  4994.5  2150.2  4996.4  2148.5  4996.6    2148  5000.4  2148.5  5016.3 2150.48
  5031.9 2153.93  5043.7 2160.39  5053.9 2164.17  5059.7 2167.11  5066.3 2171.52
  5075.6 2174.18  5081.3 2178.65  5091.8 2182.84    5103 2186.18    5131 2184.03
#Mann= 5 ,-1 , 0
  4847.1     .07       0  4979.1     .16       0  4996.4     .07       0
  5000.4     .16       0  5091.8     .07       0
Bank Sta=4996.4,5000.4
XS Rating Curve= 0 ,0
Exp/Cntr=0.3,0.1

Type RM Length L Ch R = 1 ,444     ,67,67,67
BEGIN DESCRIPTION:
Elm 59 4855
END DESCRIPTION:
XS GIS Cut Line= 3
       1520383.5      6766035.43      1520358.76       6765888.1
      1520321.02      6765749.03
#Sta/Elev= 30
  4850.6 2186.19  4867.5 2186.57  4878.4 2185.22    4919  2177.5  4933.2 2172.74
  4939.3 2168.47  4959.5 2159.47  4970.9 2154.92  4979.8 2151.47  4988.7 2149.55
  4993.8 2150.67  4997.5 2149.86  5002.6 2149.86  5020.8 2148.85  5027.7 2146.46
    5028 2145.96  5031.5 2145.96  5031.7 2146.46  5034.9 2147.25  5041.5 2150.61
  5051.9 2158.78  5062.3 2169.13  5069.5 2169.93  5072.4 2168.15  5074.7 2166.73
  5093.4  2172.4  5114.5 2177.03  5134.8 2179.06  5142.1 2180.68  5144.1 2180.68
#Mann= 5 ,-1 , 0
  4850.6     .07       0  4970.9     .16       0  5027.7     .07       0
  5031.7     .16       0  5072.4     .07       0
Bank Sta=5027.7,5031.7
XS Rating Curve= 0 ,0
Exp/Cntr=0.3,0.1

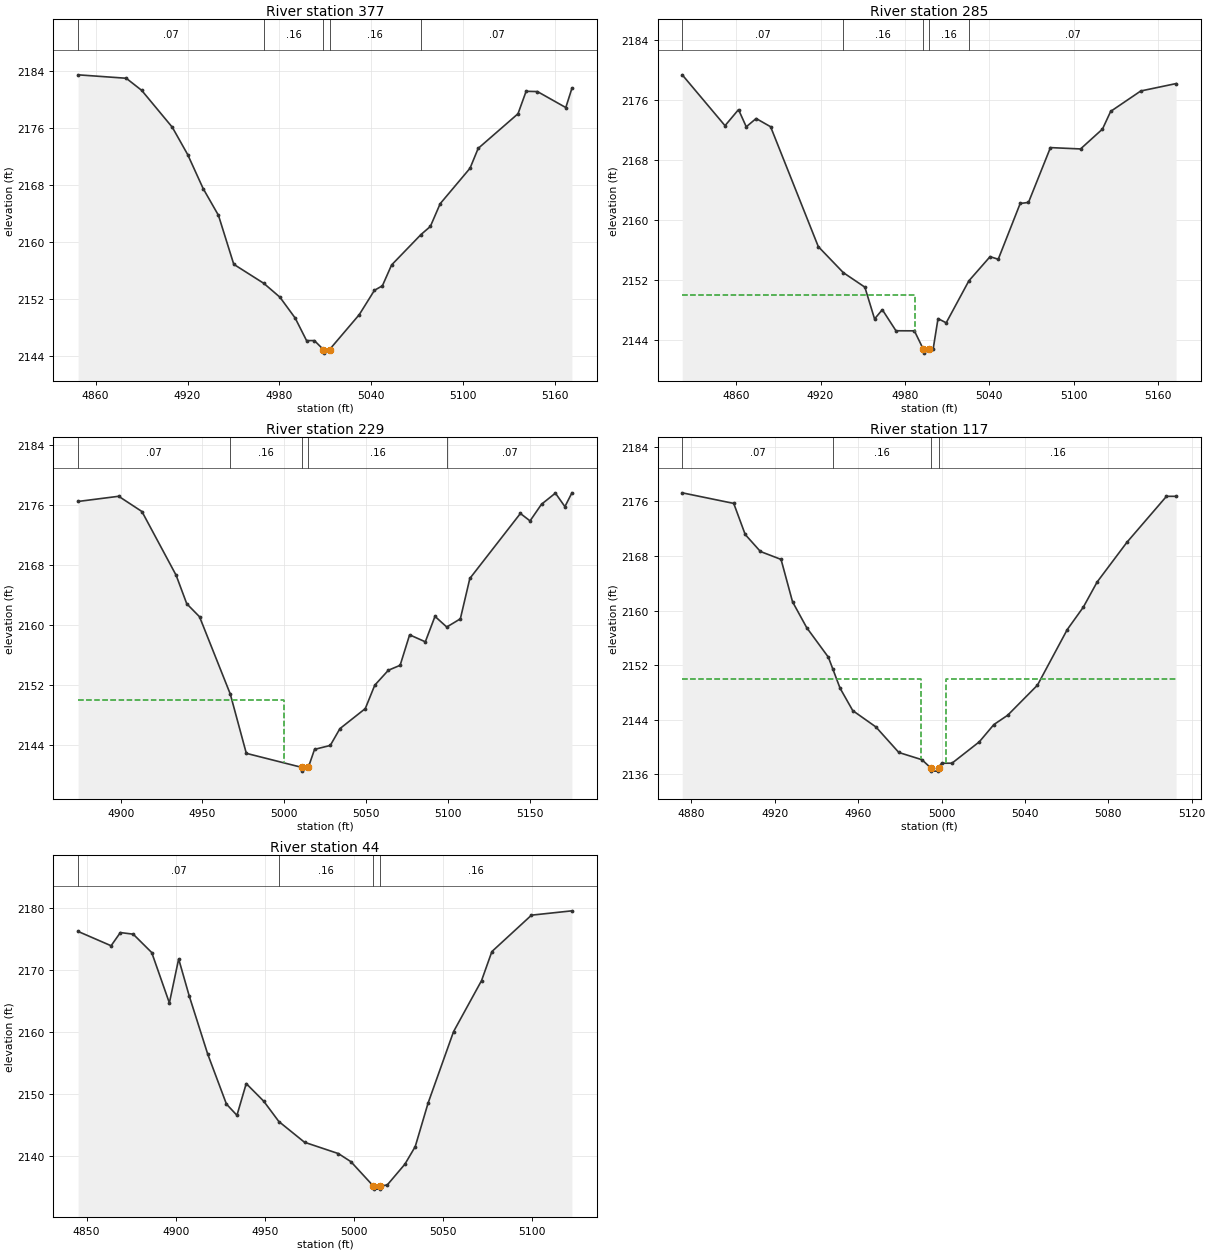
Type RM Length L Ch R = 1 ,377     ,92,92,92
BEGIN DESCRIPTION:
Elm 59 4854
END DESCRIPTION:
XS GIS Cut Line= 3
      1520414.76      6766039.37      1520425.14      6765888.33
      1520369.58      6765726.71
#Sta/Elev= 30
  4848.6 2183.49    4880 2183.01  4890.1 2181.31  4910.1 2176.13  4920.1 2172.31
  4930.2 2167.54  4940.2 2163.78  4950.2 2156.91  4969.8 2154.24  4980.3  2152.3
  4990.3 2149.36  4997.7 2146.21  5002.8 2146.21  5008.7 2144.95    5009 2144.45
  5012.7 2144.95  5032.1 2149.85    5042 2153.26  5047.2  2153.9  5053.2 2156.82
  5072.4 2161.09  5078.5 2162.22  5084.9 2165.41  5104.4 2170.39  5109.7 2173.17
  5135.7 2178.03    5141 2181.18  5148.4 2181.14  5166.9  2178.9  5170.9 2181.61
#Mann= 5 ,-1 , 0
  4848.6     .07       0  4969.8     .16       0  5008.7     .07       0
  5012.7     .16       0  5072.4     .07       0
Bank Sta=5008.7,5012.7
XS Rating Curve= 0 ,0
Exp/Cntr=0.3,0.1

Type RM Length L Ch R = 1 ,285     ,56,56,56
BEGIN DESCRIPTION:
Elm 59 4853
END DESCRIPTION:
XS GIS Cut Line= 3
       1520578.8      6766005.47      1520502.85      6765844.15
      1520414.76      6765695.61
#Sta/Elev= 30
  4821.7 2179.39  4852.1 2172.59  4861.7 2174.74  4867.2 2172.44  4874.2 2173.55
  4884.5 2172.45  4918.4 2156.42  4936.2 2152.94  4951.5    2151  4958.4 2146.75
  4963.9 2147.99  4973.6 2145.17  4986.7 2145.16  4993.1 2142.68  4993.4 2142.18
  4997.1 2142.68    5000 2142.68  5003.5  2146.8  5009.3 2146.23  5025.4 2151.84
  5040.5 2155.08  5046.3 2154.73  5061.9 2162.19  5067.8 2162.33  5083.4 2169.66
  5104.8 2169.48  5120.4 2172.14  5126.2  2174.5  5147.6 2177.23  5172.7 2178.22
#Mann= 5 ,-1 , 0
  4821.7     .07       0  4936.2     .16       0  4993.1     .07       0
  4997.1     .16       0  5025.4     .07       0
#XS Ineff= 2 , 0
       0    4987    2150               0
Permanent Ineff=
       F       F
Bank Sta=4993.1,4997.1
XS Rating Curve= 0 ,0
Exp/Cntr=0.3,0.1

Type RM Length L Ch R = 1 ,229     ,112,112,112
BEGIN DESCRIPTION:
Elm 59 4852
END DESCRIPTION:
XS GIS Cut Line= 3
      1520638.69      6765928.66      1520557.55      6765832.27
      1520466.06      6765682.15
#Sta/Elev= 30
    4874 2176.49  4898.8 2177.18    4913 2175.15  4933.9 2166.66  4940.4 2162.86
  4948.2 2161.13    4967 2150.83  4976.8 2142.93  5010.7 2141.06  5010.9 2140.56
  5014.7 2141.06  5018.5 2143.46  5028.1 2143.98    5034 2146.22  5049.5 2148.89
  5055.3 2152.01  5063.6    2154  5070.8 2154.66  5076.6 2158.72  5086.2 2157.79
  5092.1 2161.18  5099.3 2159.76  5107.6 2160.85  5113.4 2166.23  5144.3 2174.89
  5150.2  2173.9  5157.2 2176.12  5165.7  2177.6  5171.5  2175.8  5175.8 2177.64
#Mann= 5 ,-1 , 0
    4874     .07       0    4967     .16       0  5010.7     .07       0
  5014.7     .16       0  5099.3     .07       0
#XS Ineff= 2 , 0
       0    5000    2150               0
Permanent Ineff=
       F       F
Bank Sta=5010.7,5014.7
XS Rating Curve= 0 ,0
Exp/Cntr=0.3,0.1

Type RM Length L Ch R = 1 ,117     ,73,73,73
BEGIN DESCRIPTION:
Elm 59 4851
END DESCRIPTION:
XS GIS Cut Line= 3
      1520662.17       6765851.9      1520608.87       6765739.5
      1520522.86      6765666.99
#Sta/Elev= 30
  4875.6 2177.24  4900.3 2175.69  4905.8 2171.14  4913.1 2168.65    4923 2167.49
  4928.5 2161.29  4935.3  2157.5  4945.7 2153.17  4947.8 2151.47  4951.3 2148.64
  4957.4 2145.35  4968.5 2142.96  4979.5 2139.22  4990.6 2138.16  4994.7 2136.99
    4995 2136.49  4998.5 2136.49  4998.7 2136.99    5000 2137.65    5005 2137.65
  5018.1 2140.78  5025.1 2143.31  5031.7 2144.67    5046 2149.08  5060.3 2157.22
    5068  2160.5  5074.6 2164.17  5088.9 2169.99  5107.9 2176.73  5112.5 2176.73
#Mann= 4 ,-1 , 0
  4875.6     .07       0  4947.8     .16       0  4994.7     .07       0
  4998.7     .16       0
#XS Ineff= 2 , 0
       0    4990    2150    5002       0    2150
Permanent Ineff=
       F       F
Bank Sta=4994.7,4998.7
XS Rating Curve= 0 ,0
Exp/Cntr=0.3,0.1

Type RM Length L Ch R = 1 ,44      ,0,0,0
BEGIN DESCRIPTION:
Elm 59 4850
END DESCRIPTION:
XS GIS Cut Line= 3
      1520706.41      6765837.51      1520660.87      6765689.56
      1520555.37       6765627.9
#Sta/Elev= 30
  4845.2 2176.25  4863.7 2173.94  4868.9 2176.07  4876.1 2175.81  4886.5 2172.84
  4896.4  2164.7  4901.6 2171.81  4907.5 2165.86  4917.9 2156.44  4928.4 2148.37
  4934.3 2146.55  4939.5 2151.68  4949.3 2148.84  4957.8 2145.55  4972.2  2142.2
  4991.2 2140.37  4998.2 2139.07  5010.8 2135.13    5011 2134.63  5014.5 2134.63
  5014.8 2135.13  5018.6  2135.3  5028.5 2138.66  5034.3  2141.5  5041.5 2148.52
  5055.8 2160.07  5071.5 2168.31  5077.3    2173  5099.5 2178.88  5122.2 2179.58
#Mann= 4 ,-1 , 0
  4845.2     .07       0  4957.8     .16       0  5010.8     .07       0
  5014.8     .16       0
Bank Sta=5010.8,5014.8
XS Rating Curve= 0 ,0
Exp/Cntr=0.3,0.1

Chan Stop Cuts=-1
Use User Specified Reach Order=0
Composite Channel Slope=5