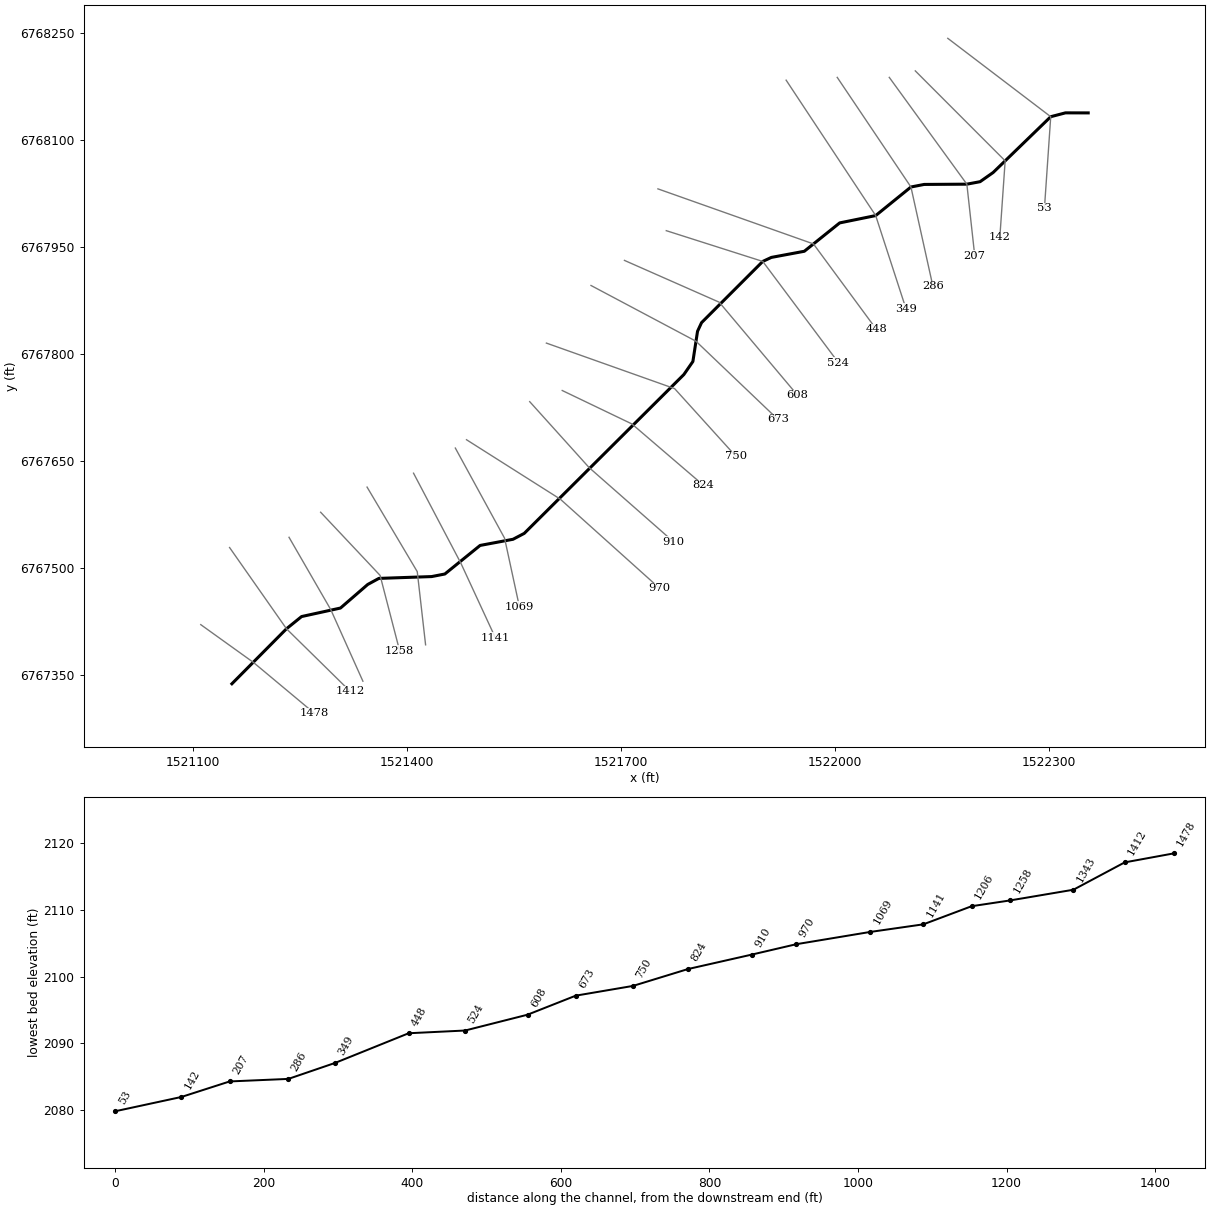
--- Elm 60.prj (project) ---

Proj Title=Elm 60 Base Level Engineering
Current Plan=p01
Default Exp/Contr=0.3,0.1
English Units
Geom File=g01
Flow File=f01
Plan File=p01
BEGIN DESCRIPTION:
Elm 60
END DESCRIPTION:

--- Elm 60.p01 (plan) ---

Plan Title=Multiple Run
Short Identifier=Multiple
Geom File=g01
Flow File=f01
Subcritical Flow
K Sum by GR= 0
Std Step Tol= 0.01
Critical Tol= 0.01
Num of Std Step Trials= 20
Max Error Tol= 0.3
Flow Tol Ratio= 0.001
Split Flow NTrial= 30
Split Flow Tol= 0.02
Split Flow Ratio= 0.02
Log Output Level= 0
Friction Slope Method= 1
Unsteady Friction Slope Method= 2
Unsteady Bridges Friction Slope Method= 1
Parabolic Critical Depth
Global Vel Dist=  1 , 1 , 1
Global Log Level= 0
CheckData=True
Encroach Param= -1, 0, 0, 0
BEGIN DESCRIPTION:
Multiple Run
END DESCRIPTION:

--- Elm 60.f01 (steady flow) ---

Flow Title=Multiple
Number of Profiles=7
Profile Names=10-year,25-year,50-year,1pct_min,100-year,1pct_plu,500-year
River Rch & RM= Elm 60,Reach-1,1478
      94     125     150     112     180     248     263
Boundary for River Rch & Prof#=Elm 60,Reach-1,1
Up Type=0
Dn Type=3
Dn Slope=0.005
Boundary for River Rch & Prof#=Elm 60,Reach-1,2
Up Type=0
Dn Type=3
Dn Slope=0.005
Boundary for River Rch & Prof#=Elm 60,Reach-1,3
Up Type=0
Dn Type=3
Dn Slope=0.005
Boundary for River Rch & Prof#=Elm 60,Reach-1,4
Up Type=0
Dn Type=3
Dn Slope=0.005
Boundary for River Rch & Prof#=Elm 60,Reach-1,5
Up Type=0
Dn Type=3
Dn Slope=0.005
Boundary for River Rch & Prof#=Elm 60,Reach-1,6
Up Type=0
Dn Type=3
Dn Slope=0.005
Boundary for River Rch & Prof#=Elm 60,Reach-1,7
Up Type=0
Dn Type=3
Dn Slope=0.005

--- Elm 60.g01 (geometry) ---

Geom Title=Existing Conditions

River Reach=Elm 60,Reach-1
Reach XY= 30
      1521155.00      6767338.00      1521193.25      6767376.54
      1521231.49      6767415.08      1521252.68      6767432.21
      1521307.17      6767444.13      1521345.35      6767477.17
      1521360.97      6767485.67      1521434.91      6767488.23
      1521453.42      6767491.83      1521502.83      6767531.86
      1521548.97      6767540.50      1521564.68      6767548.76
      1521788.35      6767771.33      1521801.02      6767789.65
      1521807.53      6767831.96      1521813.15      6767844.07
      1521898.93      6767929.87      1521911.03      6767935.50
      1521957.18      6767944.10      1522006.72      6767983.84
      1522057.18      6767994.12      1522106.59      6768034.17
      1522125.10      6768037.76      1522184.95      6768038.13
      1522203.50      6768041.61      1522221.75      6768054.46
      1522262.12      6768093.57      1522302.49      6768132.67
      1522323.12      6768138.07      1522355.00      6768138.00

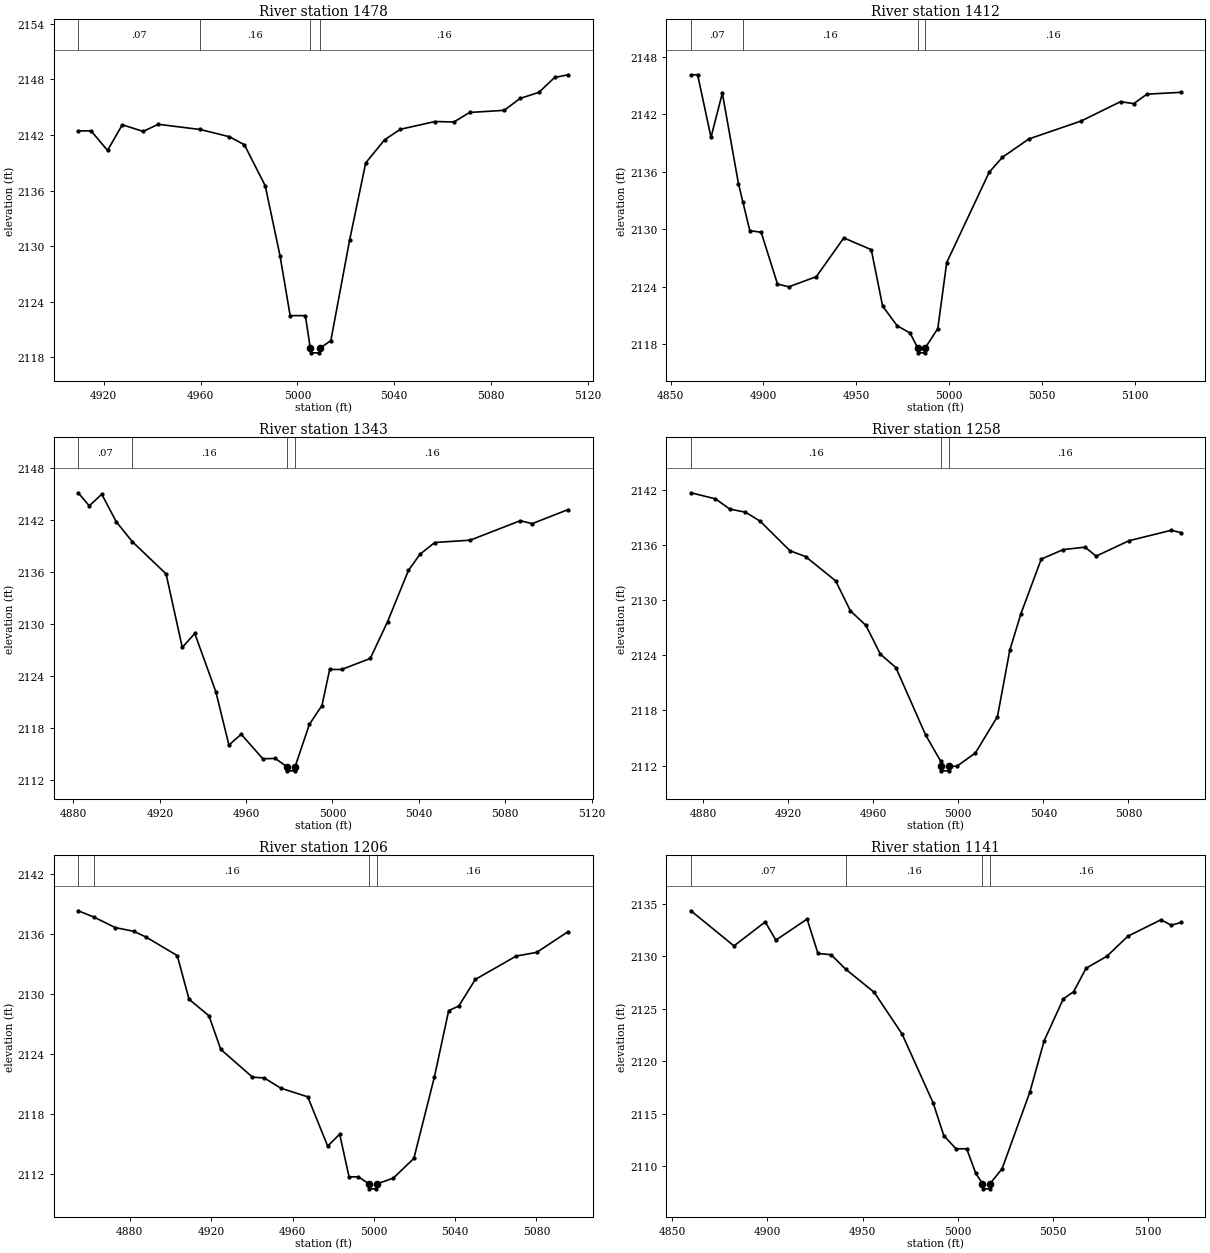
Type RM Length L Ch R = 1,1478,66,66,66
BEGIN DESCRIPTION:
Elm 60 4878
END DESCRIPTION:
XS GIS Cut Line= 3
      1521111.36      6767420.88      1521184.90      6767368.13
      1521270.76      6767296.52
#Sta/Elev= 30
  4909.5 2142.45  4914.8 2142.45  4921.6 2140.34  4927.7 2143.11  4936.3 2142.39
  4942.5 2143.16  4959.8 2142.60  4971.9 2141.82  4978.1 2140.95  4986.7 2136.52
  4992.8 2128.98  4997.0 2122.49  5003.3 2122.49  5005.3 2118.97  5005.6 2118.47
  5009.1 2118.47  5009.3 2118.97  5013.8 2119.79  5021.6 2130.71  5028.2 2138.99
  5036.0 2141.49  5042.5 2142.62  5056.8 2143.46  5064.6 2143.41  5071.1 2144.44
  5085.4 2144.67  5091.9 2145.95  5099.7 2146.61  5106.2 2148.22  5111.8 2148.51
#Mann=4,-1,0
  4909.5    0.07       0  4959.8    0.16       0  5005.3    0.07       0
  5009.3    0.16       0
Bank Sta=5005.3,5009.3
Exp/Cntr=0.3,0.1

Type RM Length L Ch R = 1,1412,69,69,69
BEGIN DESCRIPTION:
Elm 60 1412.137
END DESCRIPTION:
XS GIS Cut Line= 3
      1521151.75      6767528.93      1521231.49      6767415.08
      1521320.51      6767327.61
#Sta/Elev= 30
  4861.0 2146.10  4864.6 2146.10  4871.8 2139.58  4877.9 2144.19  4886.6 2134.73
  4888.9 2132.89  4892.7 2129.85  4898.8 2129.69  4907.6 2124.29  4913.7 2124.00
  4928.5 2125.06  4943.3 2129.10  4958.1 2127.87  4964.2 2121.99  4972.0 2119.95
  4979.0 2119.18  4983.1 2117.62  4983.4 2117.12  4986.9 2117.12  4987.1 2117.62
  4993.9 2119.65  4998.7 2126.53  5021.6 2135.95  5028.7 2137.50  5042.9 2139.41
  5071.2 2141.29  5092.3 2143.30  5099.4 2143.09  5106.5 2144.08  5124.8 2144.27
#Mann=4,-1,0
  4861.0    0.07       0  4888.9    0.16       0  4983.1    0.07       0
  4987.1    0.16       0
Bank Sta=4983.1,4987.1
Exp/Cntr=0.3,0.1

Type RM Length L Ch R = 1,1343,85,85,85
BEGIN DESCRIPTION:
Elm 60 1342.71
END DESCRIPTION:
XS GIS Cut Line= 3
      1521235.06      6767543.28      1521293.66      6767441.71
      1521338.59      6767341.59
#Sta/Elev= 30
  4882.2 2145.17  4887.3 2143.66  4893.1 2145.00  4899.8 2141.83  4907.2 2139.53
  4922.9 2135.79  4930.4 2127.29  4936.2 2128.90  4946.0 2122.13  4952.0 2116.00
  4957.7 2117.25  4967.7 2114.42  4973.5 2114.45  4978.7 2113.52  4978.9 2113.02
  4982.4 2113.02  4982.7 2113.52  4989.3 2118.40  4995.1 2120.56  4998.7 2124.74
  5004.2 2124.74  5017.5 2126.01  5025.5 2130.26  5035.2 2136.20  5040.6 2138.08
  5047.4 2139.42  5063.8 2139.69  5087.0 2141.94  5092.5 2141.60  5109.2 2143.23
#Mann=4,-1,0
  4882.2    0.07       0  4907.2    0.16       0  4978.7    0.07       0
  4982.7    0.16       0
Bank Sta=4978.7,4982.7
Exp/Cntr=0.3,0.1

Type RM Length L Ch R = 1,1258,52,52,52
BEGIN DESCRIPTION:
Elm 60 1258.06
END DESCRIPTION:
XS GIS Cut Line= 3
      1521279.37      6767578.39      1521362.67      6767489.89
      1521390.02      6767384.42
#Sta/Elev= 30
  4874.2 2141.70  4885.7 2141.04  4892.5 2139.92  4899.8 2139.59  4906.7 2138.62
  4920.8 2135.38  4928.1 2134.76  4942.3 2132.10  4949.2 2128.85  4956.5 2127.26
  4963.3 2124.13  4970.6 2122.67  4984.6 2115.33  4991.7 2112.46  4991.8 2111.92
  4992.0 2111.42  4995.5 2111.42  4995.8 2111.92  4999.3 2111.92  5008.0 2113.36
  5018.4 2117.33  5024.2 2124.56  5029.4 2128.51  5039.0 2134.48  5049.3 2135.51
  5059.6 2135.78  5064.8 2134.80  5080.3 2136.48  5100.2 2137.62  5104.7 2137.36
#Mann=3,-1,0
  4874.2    0.16       0  4991.8    0.07       0  4995.8    0.16       0
Bank Sta=4991.8,4995.8
Exp/Cntr=0.3,0.1

Type RM Length L Ch R = 1,1206,65,65,65
BEGIN DESCRIPTION:
Elm 60 1206.16
END DESCRIPTION:
XS GIS Cut Line= 3
      1521344.43      6767613.62      1521414.76      6767495.10
      1521426.44      6767392.58
#Sta/Elev= 30
  4854.6 2138.36  4862.4 2137.72  4872.8 2136.68  4881.8 2136.31  4887.7 2135.76
  4903.3 2133.88  4909.1 2129.51  4918.9 2127.86  4924.7 2124.50  4940.3 2121.72
  4946.1 2121.64  4954.2 2120.62  4967.5 2119.75  4977.3 2114.82  4983.2 2116.02
  4987.8 2111.75  4992.4 2111.75  4997.6 2111.05  4997.8 2110.55  5001.3 2110.55
  5001.6 2111.05  5009.6 2111.62  5019.7 2113.60  5029.8 2121.75  5036.8 2128.37
  5041.8 2128.84  5049.9 2131.49  5070.0 2133.83  5080.1 2134.20  5095.6 2136.28
#Mann=4,-1,0
  4854.6    0.07       0  4862.4    0.16       0  4997.6    0.07       0
  5001.6    0.16       0
Bank Sta=4997.6,5001.6
Exp/Cntr=0.3,0.1

Type RM Length L Ch R = 1,1141,72,72,72
BEGIN DESCRIPTION:
Elm 60 1140.55
END DESCRIPTION:
XS GIS Cut Line= 3
      1521409.55      6767633.11      1521475.96      6767506.81
      1521524.07      6767402.79
#Sta/Elev= 30
  4859.9 2134.35  4882.5 2131.00  4898.9 2133.29  4904.5 2131.55  4920.9 2133.56
  4926.6 2130.28  4933.5 2130.16  4941.1 2128.79  4956.1 2126.58  4970.7 2122.62
  4987.1 2116.02  4992.7 2112.90  4999.1 2111.65  5004.7 2111.65  5009.5 2109.30
  5013.0 2108.33  5013.3 2107.83  5016.8 2107.83  5017.0 2108.33  5023.3 2109.75
  5037.9 2117.07  5045.4 2121.96  5055.4 2125.94  5060.9 2126.64  5067.4 2128.87
  5078.3 2130.01  5089.4 2131.93  5106.7 2133.49  5112.2 2132.97  5117.2 2133.24
#Mann=4,-1,0
  4859.9    0.07       0  4941.1    0.16       0  5013.0    0.07       0
  5017.0    0.16       0
Bank Sta=5013,5017
Exp/Cntr=0.3,0.1

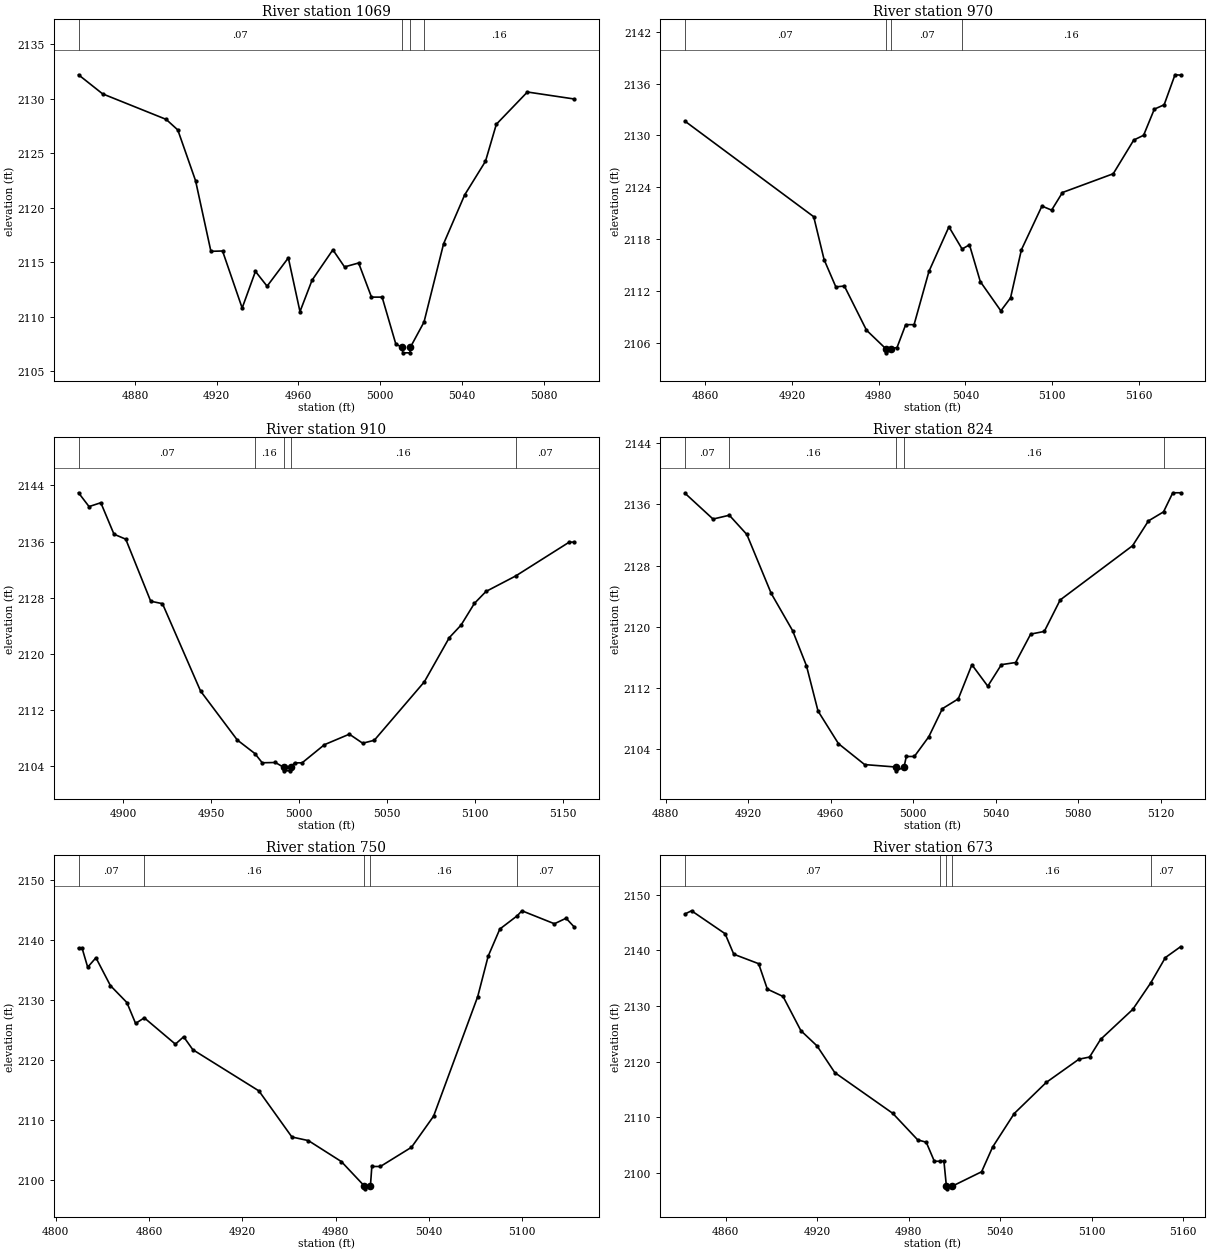
Type RM Length L Ch R = 1,1069,99,99,99
BEGIN DESCRIPTION:
Elm 60 1068.71
END DESCRIPTION:
XS GIS Cut Line= 3
      1521468.12      6767668.32      1521537.15      6767541.97
      1521558.00      6767445.57
#Sta/Elev= 30
  4852.4 2132.18  4864.2 2130.43  4895.3 2128.09  4901.0 2127.12  4909.7 2122.46
  4917.2 2115.99  4922.9 2116.02  4932.5 2110.79  4939.0 2114.15  4944.7 2112.79
  4955.1 2115.39  4960.8 2110.46  4966.7 2113.34  4976.9 2116.13  4982.6 2114.56
  4989.5 2114.92  4995.8 2111.79  5001.0 2111.79  5007.7 2107.49  5010.8 2107.18
  5011.1 2106.68  5014.6 2106.68  5014.8 2107.18  5021.5 2109.50  5031.1 2116.69
  5041.4 2121.16  5051.6 2124.25  5056.9 2127.64  5072.1 2130.60  5095.0 2129.96
#Mann=4,-1,0
  4852.4    0.07       0  5010.8    0.07       0  5014.8    0.07       0
  5021.5    0.16       0
Bank Sta=5010.8,5014.8
Exp/Cntr=0.3,0.1

Type RM Length L Ch R = 1,970,60,60,60
BEGIN DESCRIPTION:
Elm 60 970.45
END DESCRIPTION:
XS GIS Cut Line= 3
      1521483.78      6767679.99      1521615.28      6767596.66
      1521754.42      6767471.69
#Sta/Elev= 30
  4846.1 2131.65  4935.1 2120.60  4942.3 2115.63  4950.4 2112.48  4956.3 2112.58
  4971.6 2107.47  4984.8 2105.35  4985.1 2104.85  4988.8 2105.35  4992.7 2105.46
  4998.7 2108.11  5004.5 2108.11  5014.8 2114.28  5028.6 2119.43  5037.7 2116.86
  5042.8 2117.35  5050.3 2113.09  5064.5 2109.71  5071.2 2111.21  5078.7 2116.77
  5092.9 2121.83  5099.6 2121.36  5107.1 2123.40  5142.2 2125.57  5156.4 2129.47
  5163.2 2130.02  5170.6 2133.04  5177.4 2133.55  5184.9 2137.02  5188.8 2136.98
#Mann=4,-1,0
  4846.1    0.07       0  4984.8    0.07       0  4988.8    0.07       0
  5037.7    0.16       0
Bank Sta=4984.8,4988.8
Exp/Cntr=0.3,0.1

Type RM Length L Ch R = 1,910,86,86,86
BEGIN DESCRIPTION:
Elm 60 910.14
END DESCRIPTION:
XS GIS Cut Line= 3
      1521572.34      6767733.35      1521655.64      6767640.93
      1521774.14      6767536.76
#Sta/Elev= 30
  4874.4 2142.96  4880.4 2140.99  4887.1 2141.54  4894.6 2137.05  4901.3 2136.34
  4915.5 2127.49  4922.2 2127.14  4943.9 2114.67  4964.8 2107.69  4974.8 2105.76
  4979.0 2104.44  4986.5 2104.48  4991.2 2103.79  4991.5 2103.29  4995.0 2103.29
  4995.2 2103.79  4997.4 2104.43  5001.7 2104.43  5014.4 2107.02  5028.6 2108.52
  5036.2 2107.23  5042.8 2107.65  5071.3 2115.99  5085.5 2122.29  5092.2 2124.08
  5099.8 2127.18  5106.4 2128.88  5123.3 2131.09  5153.8 2135.92  5156.6 2135.92
#Mann=5,-1,0
  4874.4    0.07       0  4974.8    0.16       0  4991.2    0.07       0
  4995.2    0.16       0  5123.3    0.07       0
Bank Sta=4991.2,4995.2
Exp/Cntr=0.3,0.1

Type RM Length L Ch R = 1,824,74,74,74
BEGIN DESCRIPTION:
Elm 60 824.42
END DESCRIPTION:
XS GIS Cut Line= 3
      1521617.91      6767748.99      1521715.54      6767702.13
      1521815.77      6767616.21
#Sta/Elev= 30
  4889.4 2137.46  4903.0 2134.08  4910.9 2134.58  4919.4 2132.06  4931.2 2124.35
  4941.6 2119.46  4948.3 2114.87  4953.9 2108.95  4963.8 2104.68  4976.5 2101.94
  4991.6 2101.62  4991.9 2101.12  4995.6 2101.62  4996.7 2103.00  5000.6 2103.00
  5007.6 2105.58  5014.2 2109.26  5021.9 2110.54  5028.5 2115.01  5036.2 2112.20
  5042.8 2115.02  5049.7 2115.30  5057.0 2119.02  5063.6 2119.37  5071.3 2123.49
  5106.4 2130.59  5114.1 2133.84  5121.4 2135.02  5125.9 2137.52  5129.7 2137.52
#Mann=5,-1,0
  4889.4    0.07       0  4910.9    0.16       0  4991.6    0.07       0
  4995.6    0.16       0  5121.4    0.07       0
Bank Sta=4991.6,4995.6
Exp/Cntr=0.3,0.1

Type RM Length L Ch R = 1,750,77,77,77
BEGIN DESCRIPTION:
Elm 60 749.57
END DESCRIPTION:
XS GIS Cut Line= 3
      1521595.73      6767815.42      1521775.44      6767751.61
      1521861.35      6767656.72
#Sta/Elev= 30
  4814.7 2138.65  4817.0 2138.65  4820.6 2135.48  4825.9 2137.05  4835.2 2132.42
  4845.8 2129.60  4851.4 2126.12  4857.0 2127.05  4877.0 2122.67  4882.3 2123.90
  4888.2 2121.75  4930.7 2114.89  4951.9 2107.22  4962.5 2106.62  4983.7 2103.13
  4998.4 2099.09  4998.7 2098.59  5002.4 2099.09  5003.3 2102.31  5008.8 2102.31
  5028.8 2105.51  5043.0 2110.68  5071.4 2130.60  5078.1 2137.31  5085.6 2141.83
  5096.8 2144.04  5099.8 2144.87  5120.7 2142.71  5128.2 2143.63  5133.4 2142.18
#Mann=5,-1,0
  4814.7    0.07       0  4857.0    0.16       0  4998.4    0.07       0
  5002.4    0.16       0  5096.8    0.07       0
Bank Sta=4998.4,5002.4
Exp/Cntr=0.3,0.1

Type RM Length L Ch R = 1,673,65,65,65
BEGIN DESCRIPTION:
Elm 60 673.2
END DESCRIPTION:
XS GIS Cut Line= 3
      1521658.24      6767896.14      1521805.38      6767818.01
      1521919.97      6767708.64
#Sta/Elev= 30
  4833.4 2146.54  4837.7 2147.11  4859.7 2142.99  4865.4 2139.30  4881.7 2137.60
  4887.4 2133.03  4897.7 2131.71  4909.4 2125.56  4920.0 2122.82  4931.6 2118.03
  4969.6 2110.71  4986.0 2105.93  4991.6 2105.51  4996.9 2102.09  5000.8 2102.09
  5003.2 2102.09  5004.8 2097.63  5005.1 2097.13  5008.8 2097.63  5027.9 2100.20
  5035.1 2104.63  5049.3 2110.67  5070.3 2116.26  5091.7 2120.43  5098.7 2120.82
  5105.9 2123.99  5127.0 2129.38  5138.8 2134.15  5148.4 2138.70  5158.4 2140.66
#Mann=5,-1,0
  4833.4    0.07       0  5000.8    0.16       0  5004.8    0.07       0
  5008.8    0.16       0  5138.8    0.07       0
Bank Sta=5004.8,5008.8
Exp/Cntr=0.3,0.1

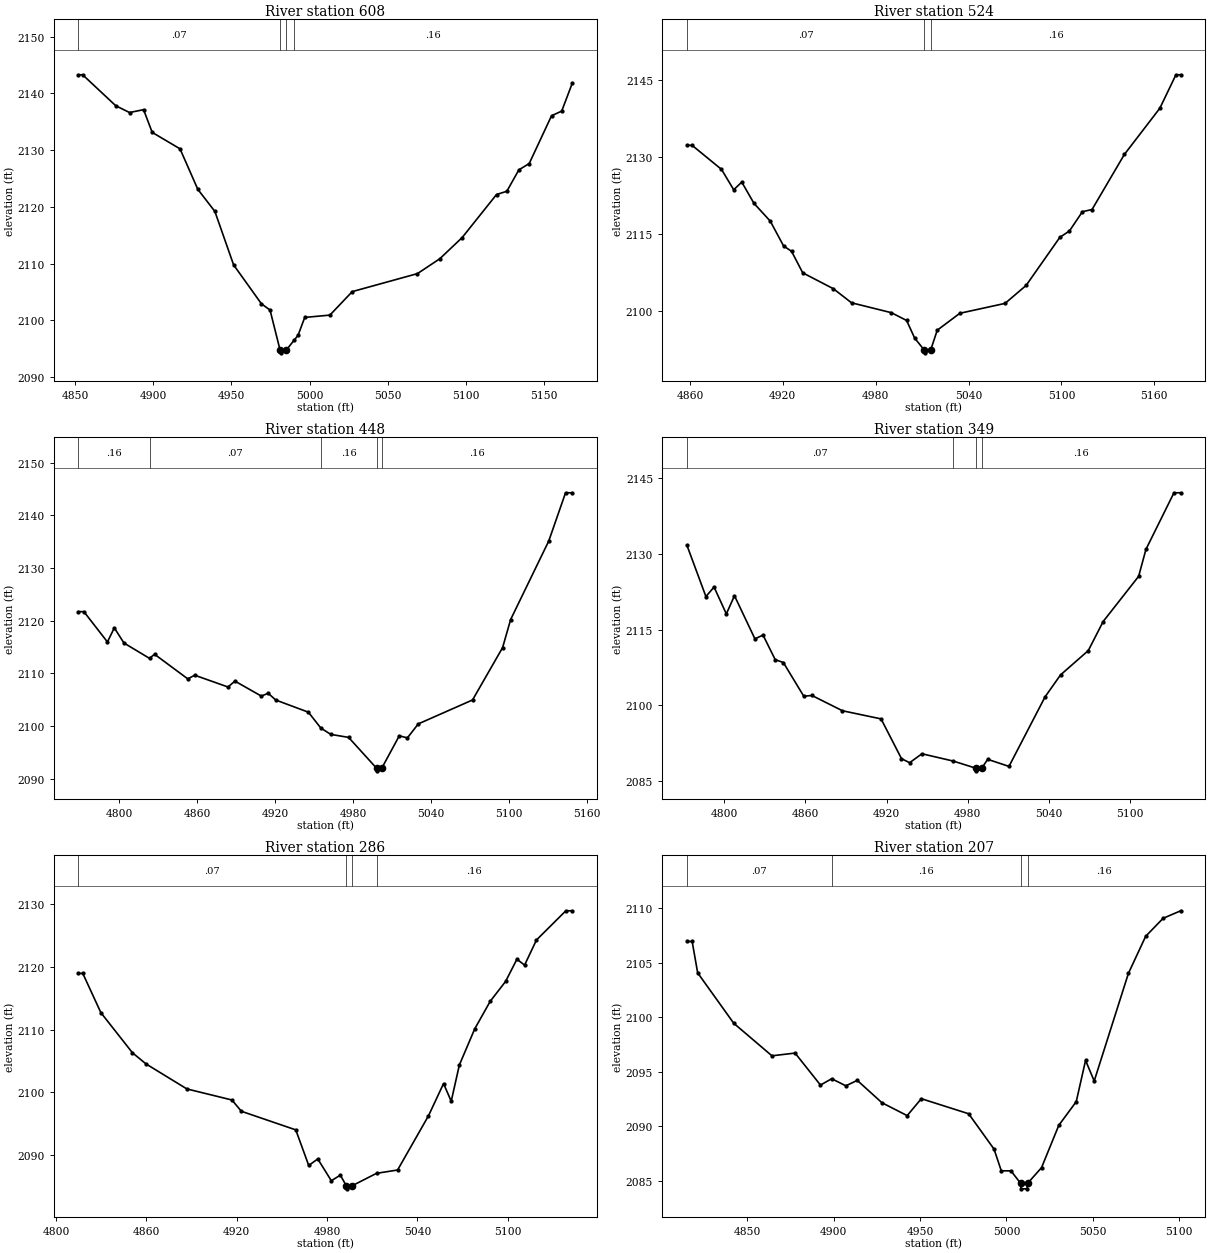
Type RM Length L Ch R = 1,608,84,84,84
BEGIN DESCRIPTION:
Elm 60 608.2
END DESCRIPTION:
XS GIS Cut Line= 3
      1521705.11      6767931.30      1521837.94      6767872.70
      1521947.87      6767742.07
#Sta/Elev= 30
  4852.1 2143.27  4854.8 2143.27  4876.0 2137.81  4884.8 2136.62  4893.8 2137.12
  4899.3 2133.12  4917.1 2130.22  4928.5 2123.08  4939.4 2119.19  4951.4 2109.76
  4969.2 2102.91  4974.7 2101.81  4981.1 2094.77  4981.4 2094.27  4985.1 2094.77
  4990.1 2096.49  4992.6 2097.35  4996.9 2100.51  5013.0 2100.92  5027.3 2105.06
  5069.0 2108.23  5083.3 2110.85  5097.6 2114.58  5119.6 2122.17  5126.2 2122.74
  5133.9 2126.52  5140.5 2127.62  5154.8 2136.05  5161.3 2136.87  5168.0 2141.74
#Mann=4,-1,0
  4852.1    0.07       0  4981.1    0.07       0  4985.1    0.07       0
  4990.1    0.16       0
Bank Sta=4981.1,4985.1
Exp/Cntr=0.3,0.1

Type RM Length L Ch R = 1,524,76,76,76
BEGIN DESCRIPTION:
Elm 60 524.421
END DESCRIPTION:
XS GIS Cut Line= 3
      1521763.73      6767972.96      1521898.93      6767929.87
      1522004.98      6767788.03
#Sta/Elev= 30
  4858.1 2132.24  4861.4 2132.24  4880.4 2127.56  4888.3 2123.60  4893.5 2125.09
  4901.4 2120.95  4911.9 2117.51  4920.5 2112.69  4925.7 2111.62  4932.9 2107.45
  4952.7 2104.36  4964.4 2101.63  4990.2 2099.70  5000.0 2098.19  5005.2 2094.77
  5011.5 2092.40  5011.8 2091.90  5015.5 2092.40  5019.8 2096.30  5034.4 2099.59
  5063.6 2101.51  5077.2 2105.00  5099.0 2114.35  5105.2 2115.59  5113.6 2119.34
  5119.8 2119.76  5140.7 2130.47  5163.6 2139.44  5174.0 2145.95  5177.1 2145.95
#Mann=3,-1,0
  4858.1    0.07       0  5011.5    0.07       0  5015.5    0.16       0
Bank Sta=5011.5,5015.5
Exp/Cntr=0.3,0.1

Type RM Length L Ch R = 1,448,99,99,99
BEGIN DESCRIPTION:
Elm 60 4875
END DESCRIPTION:
XS GIS Cut Line= 3
      1521752.04      6768031.54      1521969.99      6767954.38
      1522058.01      6767834.90
#Sta/Elev= 30
  4768.8 2121.70  4773.0 2121.70  4791.1 2115.95  4796.4 2118.62  4803.8 2115.75
  4823.5 2112.83  4827.3 2113.62  4852.9 2108.94  4858.2 2109.64  4883.8 2107.40
  4889.1 2108.52  4909.4 2105.68  4914.7 2106.21  4920.5 2104.93  4945.6 2102.62
  4955.2 2099.60  4962.9 2098.40  4976.5 2097.84  4998.0 2091.99  4998.2 2091.49
  5002.0 2091.99  5015.5 2098.14  5021.7 2097.74  5030.1 2100.40  5071.8 2104.94
  5094.9 2114.87  5101.1 2120.21  5130.4 2135.11  5143.3 2144.26  5148.4 2144.26
#Mann=5,-1,0
  4768.8    0.16       0  4823.5    0.07       0  4955.2    0.16       0
  4998.0    0.07       0  5002.0    0.16       0
Bank Sta=4998,5002
Exp/Cntr=0.3,0.1

Type RM Length L Ch R = 1,349,63,63,63
BEGIN DESCRIPTION:
Elm 60 4874
END DESCRIPTION:
XS GIS Cut Line= 3
      1521931.70      6768183.88      1522057.18      6767994.12
      1522099.66      6767863.55
#Sta/Elev= 30
  4772.5 2131.70  4786.5 2121.56  4792.5 2123.45  4801.6 2118.13  4807.6 2121.73
  4822.7 2113.19  4828.7 2113.93  4837.7 2109.06  4843.7 2108.50  4858.8 2101.82
  4864.8 2101.97  4887.4 2098.94  4915.9 2097.33  4931.0 2089.45  4937.0 2088.65
  4946.1 2090.42  4969.3 2088.97  4986.2 2087.54  4986.4 2087.04  4990.2 2087.54
  4994.7 2089.32  5010.4 2087.92  5037.1 2101.71  5048.5 2106.04  5069.0 2110.86
  5080.0 2116.62  5106.2 2125.57  5111.6 2130.91  5132.3 2142.12  5137.3 2142.12
#Mann=4,-1,0
  4772.5    0.07       0  4969.3    0.16       0  4986.2    0.07       0
  4990.2    0.16       0
Bank Sta=4986.2,4990.2
Exp/Cntr=0.3,0.1

Type RM Length L Ch R = 1,286,79,79,79
BEGIN DESCRIPTION:
Elm 60 4873
END DESCRIPTION:
XS GIS Cut Line= 3
      1522003.31      6768187.78      1522106.59      6768034.17
      1522137.41      6767894.84
#Sta/Elev= 30
  4814.9 2118.95  4817.8 2118.95  4829.8 2112.70  4850.8 2106.30  4859.8 2104.53
  4886.9 2100.55  4916.8 2098.79  4923.1 2096.99  4959.2 2094.03  4967.8 2088.36
  4973.8 2089.40  4982.8 2085.93  4988.8 2086.82  4992.7 2085.14  4992.9 2084.64
  4996.7 2085.14  5012.8 2087.11  5026.8 2087.64  5047.3 2096.27  5057.3 2101.40
  5062.4 2098.59  5067.8 2104.36  5078.0 2110.11  5088.3 2114.51  5098.5 2117.67
  5106.0 2121.20  5111.1 2120.27  5119.0 2124.27  5138.5 2128.92  5142.7 2128.92
#Mann=4,-1,0
  4814.9    0.07       0  4992.7    0.07       0  4996.7    0.07       0
  5012.8    0.16       0
Bank Sta=4992.7,4996.7
Exp/Cntr=0.3,0.1

Type RM Length L Ch R = 1,207,65,65,65
BEGIN DESCRIPTION:
Elm 60 4872
END DESCRIPTION:
XS GIS Cut Line= 3
      1522076.22      6768187.80      1522184.95      6768038.13
      1522196.00      6767937.84
#Sta/Elev= 30
  4815.0 2106.93  4818.0 2106.93  4821.2 2104.05  4842.1 2099.43  4864.2 2096.45
  4877.6 2096.70  4892.3 2093.77  4898.8 2094.35  4907.0 2093.70  4913.6 2094.20
  4927.9 2092.15  4942.5 2090.97  4950.7 2092.52  4978.1 2091.14  4992.8 2087.90
  4997.0 2085.91  5002.6 2085.91  5008.2 2084.76  5008.4 2084.26  5011.9 2084.26
  5012.2 2084.76  5020.3 2086.20  5030.3 2090.08  5040.4 2092.25  5045.8 2096.03
  5050.8 2094.14  5070.6 2104.00  5080.6 2107.40  5090.7 2109.05  5100.9 2109.74
#Mann=4,-1,0
  4815.0    0.07       0  4898.8    0.16       0  5008.2    0.07       0
  5012.2    0.16       0
Bank Sta=5008.2,5012.2
Exp/Cntr=0.3,0.1

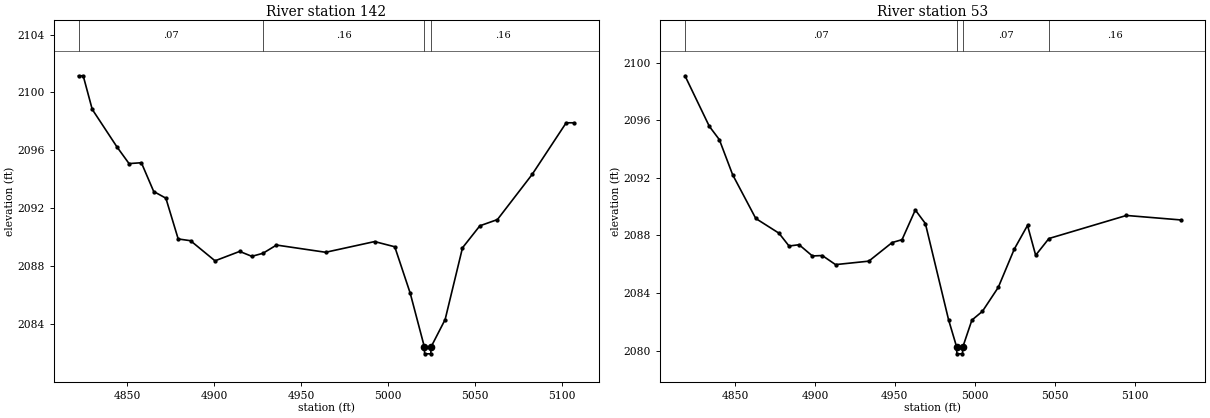
Type RM Length L Ch R = 1,142,89,89,89
BEGIN DESCRIPTION:
Elm 60 4871
END DESCRIPTION:
XS GIS Cut Line= 3
      1522112.70      6768196.89      1522238.63      6768070.81
      1522231.17      6767963.87
#Sta/Elev= 30
  4821.8 2101.15  4824.5 2101.15  4829.7 2098.83  4843.9 2096.24  4850.9 2095.08
  4858.0 2095.14  4865.1 2093.15  4872.1 2092.69  4879.2 2089.87  4886.3 2089.75
  4900.4 2088.36  4914.6 2089.01  4921.6 2088.67  4928.0 2088.88  4935.8 2089.45
  4964.1 2088.95  4992.3 2089.69  5003.9 2089.33  5012.8 2086.12  5020.9 2082.43
  5021.1 2081.93  5024.6 2081.93  5024.9 2082.43  5032.9 2084.30  5042.9 2089.26
  5052.9 2090.78  5063.0 2091.21  5083.0 2094.33  5102.6 2097.90  5107.2 2097.90
#Mann=4,-1,0
  4821.8    0.07       0  4928.0    0.16       0  5020.9    0.07       0
  5024.9    0.16       0
Bank Sta=5020.9,5024.9
Exp/Cntr=0.3,0.1

Type RM Length L Ch R = 1,53,0,0,0
BEGIN DESCRIPTION:
Elm 60 4870
END DESCRIPTION:
XS GIS Cut Line= 3
      1522158.24      6768242.50      1522302.49      6768132.67
      1522293.66      6768004.17
#Sta/Elev= 30
  4818.7 2099.08  4833.9 2095.58  4840.2 2094.65  4848.5 2092.22  4863.0 2089.18
  4877.5 2088.16  4883.8 2087.27  4890.1 2087.36  4898.4 2086.58  4904.6 2086.61
  4912.9 2085.98  4933.7 2086.22  4948.3 2087.51  4954.5 2087.71  4962.8 2089.77
  4969.1 2088.83  4983.6 2082.16  4988.6 2080.29  4988.8 2079.79  4992.3 2079.79
  4992.6 2080.29  4998.2 2082.13  5004.8 2082.74  5014.7 2084.40  5024.7 2087.05
  5033.0 2088.70  5038.1 2086.63  5046.4 2087.79  5094.9 2089.39  5128.8 2089.08
#Mann=4,-1,0
  4818.7    0.07       0  4988.6    0.07       0  4992.6    0.07       0
  5046.4    0.16       0
Bank Sta=4988.6,4992.6
Exp/Cntr=0.3,0.1

Chan Stop Cuts=-1