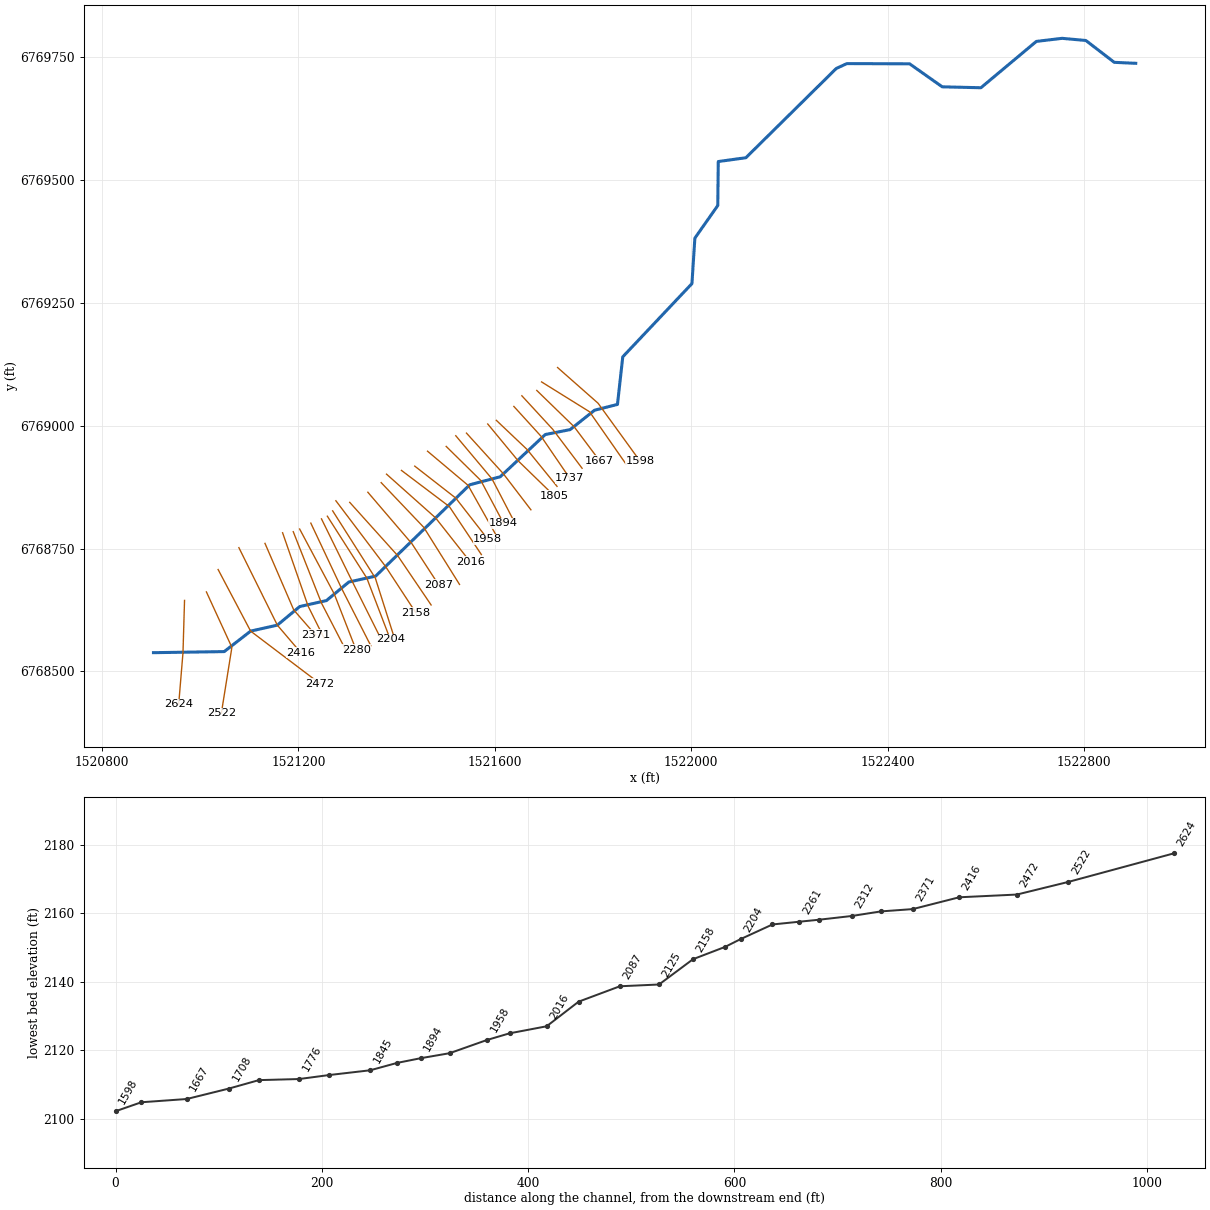
--- Elm 61.prj (project) ---

Proj Title=Elm 61 Base Level Engineering
Current Plan=p01
Default Exp/Contr=0.3,0.1
English Units
Geom File=g01
Flow File=f01
Plan File=p01
BEGIN DESCRIPTION:
Elm 61
END DESCRIPTION:

--- Elm 61.p01 (plan) ---

Plan Title=Multiple Run
Short Identifier=Multiple
Geom File=g01
Flow File=f01
Subcritical Flow
K Sum by GR= 0
Std Step Tol= 0.01
Critical Tol= 0.01
Num of Std Step Trials= 20
Max Error Tol= 0.3
Flow Tol Ratio= 0.001
Split Flow NTrial= 30
Split Flow Tol= 0.02
Split Flow Ratio= 0.02
Log Output Level= 0
Friction Slope Method= 1
Unsteady Friction Slope Method= 2
Unsteady Bridges Friction Slope Method= 1
Parabolic Critical Depth
Global Vel Dist=  1 , 1 , 1
Global Log Level= 0
CheckData=True
Encroach Param= -1, 0, 0, 0
BEGIN DESCRIPTION:
Multiple Run
END DESCRIPTION:

--- Elm 61.f01 (steady flow) ---

Flow Title=Multiple
Number of Profiles=7
Profile Names=10-year,25-year,50-year,1pct_min,100-year,1pct_plu,500-year
River Rch & RM= Elm 61,Reach-1,2624
      38      47      54      38      62      85      81
River Rch & RM= Elm 61,Reach-1,1042
      62      80      94      69     110     152     154
River Rch & RM= Elm 61,Reach-1,575
     106     141     171     129     206     284     303
Boundary for River Rch & Prof#=Elm 61,Reach-1,1
Up Type=0
Dn Type=3
Dn Slope=0.005
Boundary for River Rch & Prof#=Elm 61,Reach-1,2
Up Type=0
Dn Type=3
Dn Slope=0.005
Boundary for River Rch & Prof#=Elm 61,Reach-1,3
Up Type=0
Dn Type=3
Dn Slope=0.005
Boundary for River Rch & Prof#=Elm 61,Reach-1,4
Up Type=0
Dn Type=3
Dn Slope=0.005
Boundary for River Rch & Prof#=Elm 61,Reach-1,5
Up Type=0
Dn Type=3
Dn Slope=0.005
Boundary for River Rch & Prof#=Elm 61,Reach-1,6
Up Type=0
Dn Type=3
Dn Slope=0.005
Boundary for River Rch & Prof#=Elm 61,Reach-1,7
Up Type=0
Dn Type=3
Dn Slope=0.005

--- Elm 61.g01 (geometry) ---

Geom Title=Existing Conditions

River Reach=Elm 61,Reach-1
Reach XY= 30
      1520905.00      6768538.00      1521049.09      6768540.20
      1521102.82      6768581.88      1521157.20      6768594.08
      1521202.80      6768631.92      1521257.20      6768644.08
      1521302.81      6768681.90      1521357.30      6768693.83
      1521548.95      6768879.84      1521611.04      6768896.18
      1521702.71      6768982.15      1521753.30      6768992.18
      1521803.20      6769031.74      1521849.75      6769043.44
      1521860.55      6769140.37      1522001.39      6769289.50
      1522007.34      6769382.03      1522053.98      6769448.42
      1522055.00      6769538.00      1522111.21      6769545.76
      1522295.21      6769727.49      1522316.84      6769737.41
      1522444.58      6769736.98      1522510.97      6769690.14
      1522589.78      6769688.25      1522702.58      6769782.59
      1522754.98      6769788.86      1522803.47      6769784.48
      1522861.27      6769739.99      1522905.00      6769738.00

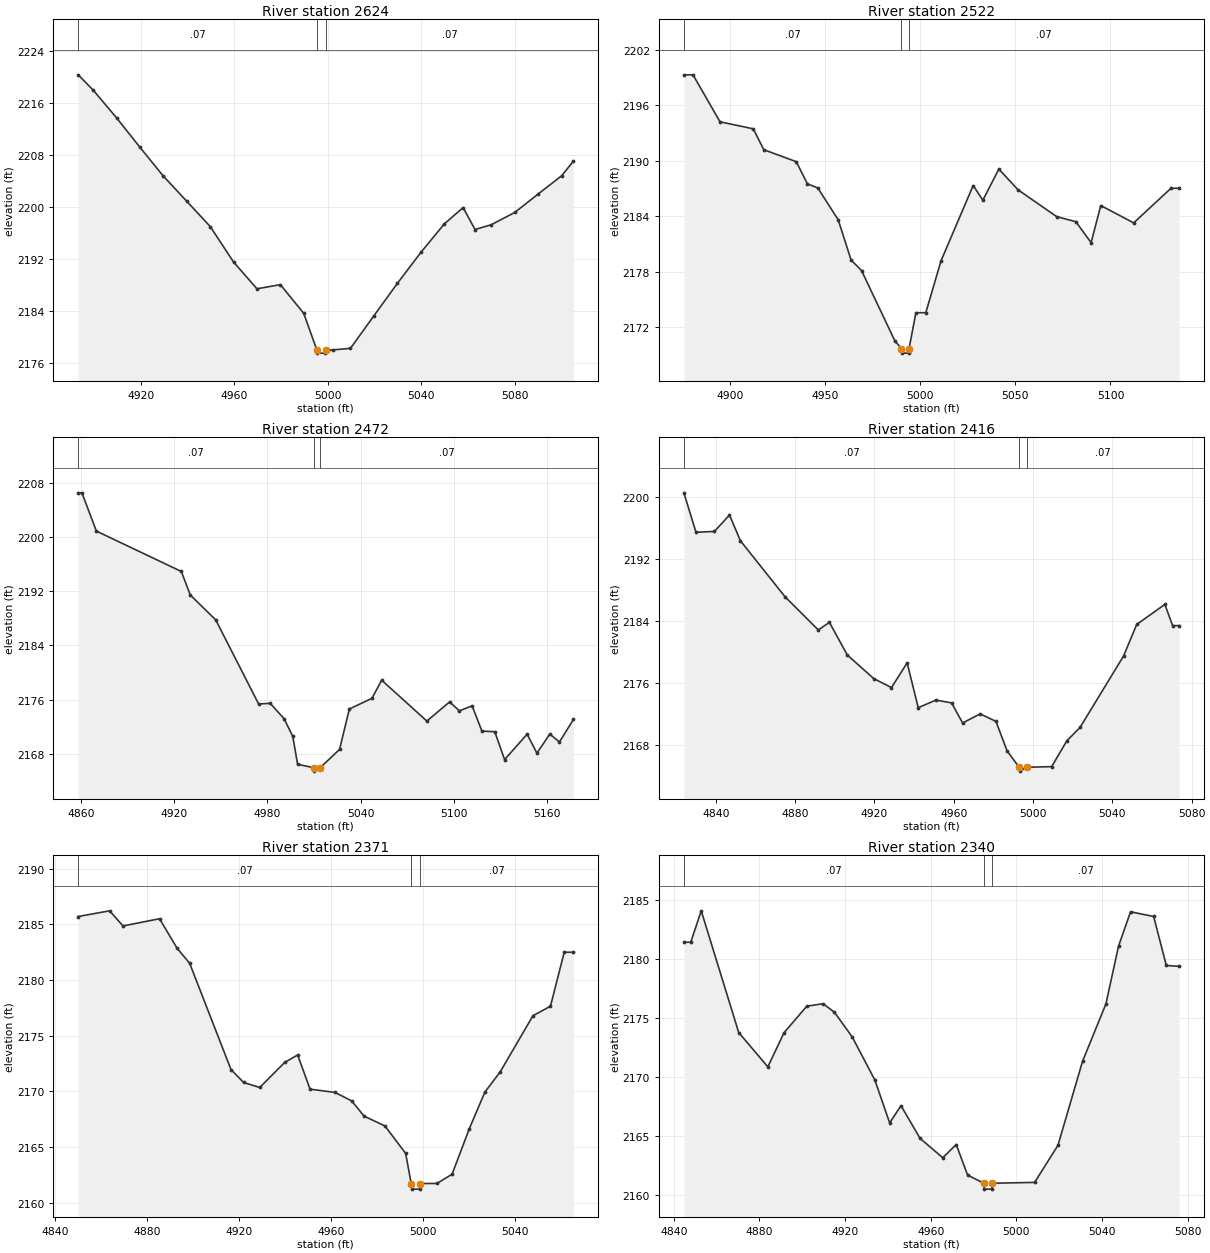
Type RM Length L Ch R = 1,2624,102,102,102
BEGIN DESCRIPTION:
Elm 61 4957
END DESCRIPTION:
XS GIS Cut Line= 3
      1520968.25      6768644.43      1520965.09      6768537.78
      1520956.33      6768432.94
#Sta/Elev= 29
  4893.3 2220.39  4899.7 2218.04  4909.7 2213.77  4919.7 2209.23  4929.7 2204.79
  4939.8 2200.88  4949.8 2197.00  4959.8 2191.52  4969.8 2187.40  4979.8 2188.04
  4989.8 2183.62  4995.4 2177.98  4995.6 2177.48  4999.1 2177.48  4999.4 2177.98
  5000.0 2177.98  5002.4 2177.98  5009.8 2178.22  5019.8 2183.22  5029.9 2188.25
  5039.9 2193.00  5050.0 2197.42  5058.0 2199.92  5063.1 2196.54  5070.0 2197.27
  5080.1 2199.17  5090.1 2202.01  5100.1 2204.81  5105.2 2207.08
#Mann=3,-1,0
  4893.3    0.07       0  4995.4    0.07       0  4999.4    0.07       0
Bank Sta=4995.4,4999.4
Exp/Cntr=0.3,0.1

Type RM Length L Ch R = 1,2522,50,50,50
BEGIN DESCRIPTION:
Elm 61 4958
END DESCRIPTION:
XS GIS Cut Line= 3
      1521012.76      6768661.73      1521064.67      6768548.79
      1521043.13      6768414.41
#Sta/Elev= 30
  4875.7 2199.31  4880.5 2199.31  4894.7 2194.22  4912.2 2193.46  4917.7 2191.20
  4934.8 2189.90  4940.6 2187.51  4946.1 2187.05  4956.8 2183.62  4963.6 2179.25
  4969.1 2178.11  4986.6 2170.50  4990.1 2169.66  4990.3 2169.16  4993.8 2169.16
  4994.1 2169.66  4997.7 2173.54  5002.9 2173.54  5010.9 2179.16  5027.8 2187.32
  5032.9 2185.73  5041.3 2189.10  5051.4 2186.85  5071.7 2183.95  5081.8 2183.40
  5089.8 2181.13  5094.9 2185.15  5112.2 2183.27  5131.8 2187.02  5136.1 2187.02
#Mann=3,-1,0
  4875.7    0.07       0  4990.1    0.07       0  4994.1    0.07       0
Bank Sta=4990.1,4994.1
Exp/Cntr=0.3,0.1

Type RM Length L Ch R = 1,2472,56,56,56
BEGIN DESCRIPTION:
Elm 61 4959
END DESCRIPTION:
XS GIS Cut Line= 3
      1521036.63      6768707.29      1521102.82      6768581.88
      1521243.87      6768475.12
#Sta/Elev= 30
  4858.2 2206.50  4860.6 2206.50  4869.9 2200.86  4924.6 2194.90  4930.3 2191.44
  4946.7 2187.77  4974.3 2175.37  4981.8 2175.45  4990.7 2173.19  4996.3 2170.58
  4999.4 2166.47  5009.9 2165.96  5010.1 2165.46  5013.9 2165.96  5026.4 2168.66
  5032.7 2174.62  5047.2 2176.19  5053.5 2178.87  5082.6 2172.84  5097.2 2175.67
  5103.5 2174.35  5111.7 2175.09  5118.0 2171.37  5126.3 2171.27  5132.6 2167.16
  5147.1 2170.91  5153.4 2168.11  5161.7 2170.93  5167.9 2169.76  5176.9 2173.08
#Mann=3,-1,0
  4858.2    0.07       0  5009.9    0.07       0  5013.9    0.07       0
Bank Sta=5009.9,5013.9
Exp/Cntr=0.3,0.1

Type RM Length L Ch R = 1,2416,45,45,45
BEGIN DESCRIPTION:
Elm 61 2416.047
END DESCRIPTION:
XS GIS Cut Line= 3
      1521078.93      6768751.83      1521157.20      6768594.08
      1521205.01      6768537.99
#Sta/Elev= 30
  4823.9 2200.50  4830.0 2195.42  4839.3 2195.53  4846.9 2197.64  4852.4 2194.33
  4874.9 2187.12  4891.7 2182.84  4897.3 2183.82  4906.3 2179.62  4919.7 2176.57
  4928.6 2175.42  4936.5 2178.60  4942.1 2172.83  4951.0 2173.81  4958.9 2173.45
  4964.5 2170.86  4973.3 2172.03  4981.3 2171.07  4986.9 2167.27  4993.0 2165.16
  4993.3 2164.66  4997.0 2165.16  5009.4 2165.24  5017.1 2168.58  5023.7 2170.28
  5045.7 2179.50  5052.3 2183.55  5066.5 2186.13  5070.4 2183.40  5073.7 2183.40
#Mann=3,-1,0
  4823.9    0.07       0  4993.0    0.07       0  4997.0    0.07       0
Bank Sta=4993,4997
Exp/Cntr=0.3,0.1

Type RM Length L Ch R = 1,2371,31,31,31
BEGIN DESCRIPTION:
Elm 61 2370.55
END DESCRIPTION:
XS GIS Cut Line= 3
      1521132.08      6768760.54      1521190.69      6768624.87
      1521235.20      6768573.85
#Sta/Elev= 30
  4849.9 2185.70  4863.6 2186.21  4869.4 2184.85  4885.3 2185.50  4892.9 2182.86
  4898.4 2181.50  4916.4 2171.95  4921.9 2170.79  4928.9 2170.34  4939.8 2172.60
  4945.4 2173.26  4950.8 2170.19  4961.6 2169.90  4968.9 2169.14  4974.3 2167.77
  4983.4 2166.88  4992.4 2164.42  4994.8 2161.71  4995.1 2161.21  4998.6 2161.21
  4998.8 2161.71  5006.0 2161.72  5012.6 2162.55  5020.1 2166.64  5026.9 2169.94
  5033.5 2171.73  5047.8 2176.79  5055.4 2177.64  5061.4 2182.49  5065.4 2182.49
#Mann=3,-1,0
  4849.9    0.07       0  4994.8    0.07       0  4998.8    0.07       0
Bank Sta=4994.8,4998.8
Exp/Cntr=0.3,0.1

Type RM Length L Ch R = 1,2340,28,28,28
BEGIN DESCRIPTION:
Elm 61 2340.27
END DESCRIPTION:
XS GIS Cut Line= 3
      1521167.91      6768782.20      1521219.99      6768632.47
      1521252.53      6768567.38
#Sta/Elev= 30
  4844.7 2181.45  4847.9 2181.45  4852.8 2184.11  4870.3 2173.80  4883.9 2170.89
  4891.5 2173.79  4902.1 2176.03  4909.7 2176.24  4915.0 2175.52  4923.3 2173.43
  4933.9 2169.77  4940.8 2166.14  4946.1 2167.60  4955.0 2164.83  4965.6 2163.19
  4971.9 2164.31  4977.2 2161.72  4984.8 2161.03  4985.0 2160.53  4988.5 2160.53
  4988.8 2161.03  5008.5 2161.10  5019.4 2164.24  5030.9 2171.37  5041.8 2176.22
  5047.7 2181.12  5053.3 2184.03  5064.1 2183.63  5070.0 2179.48  5076.0 2179.41
#Mann=3,-1,0
  4844.7    0.07       0  4984.8    0.07       0  4988.8    0.07       0
Bank Sta=4984.8,4988.8
Exp/Cntr=0.3,0.1

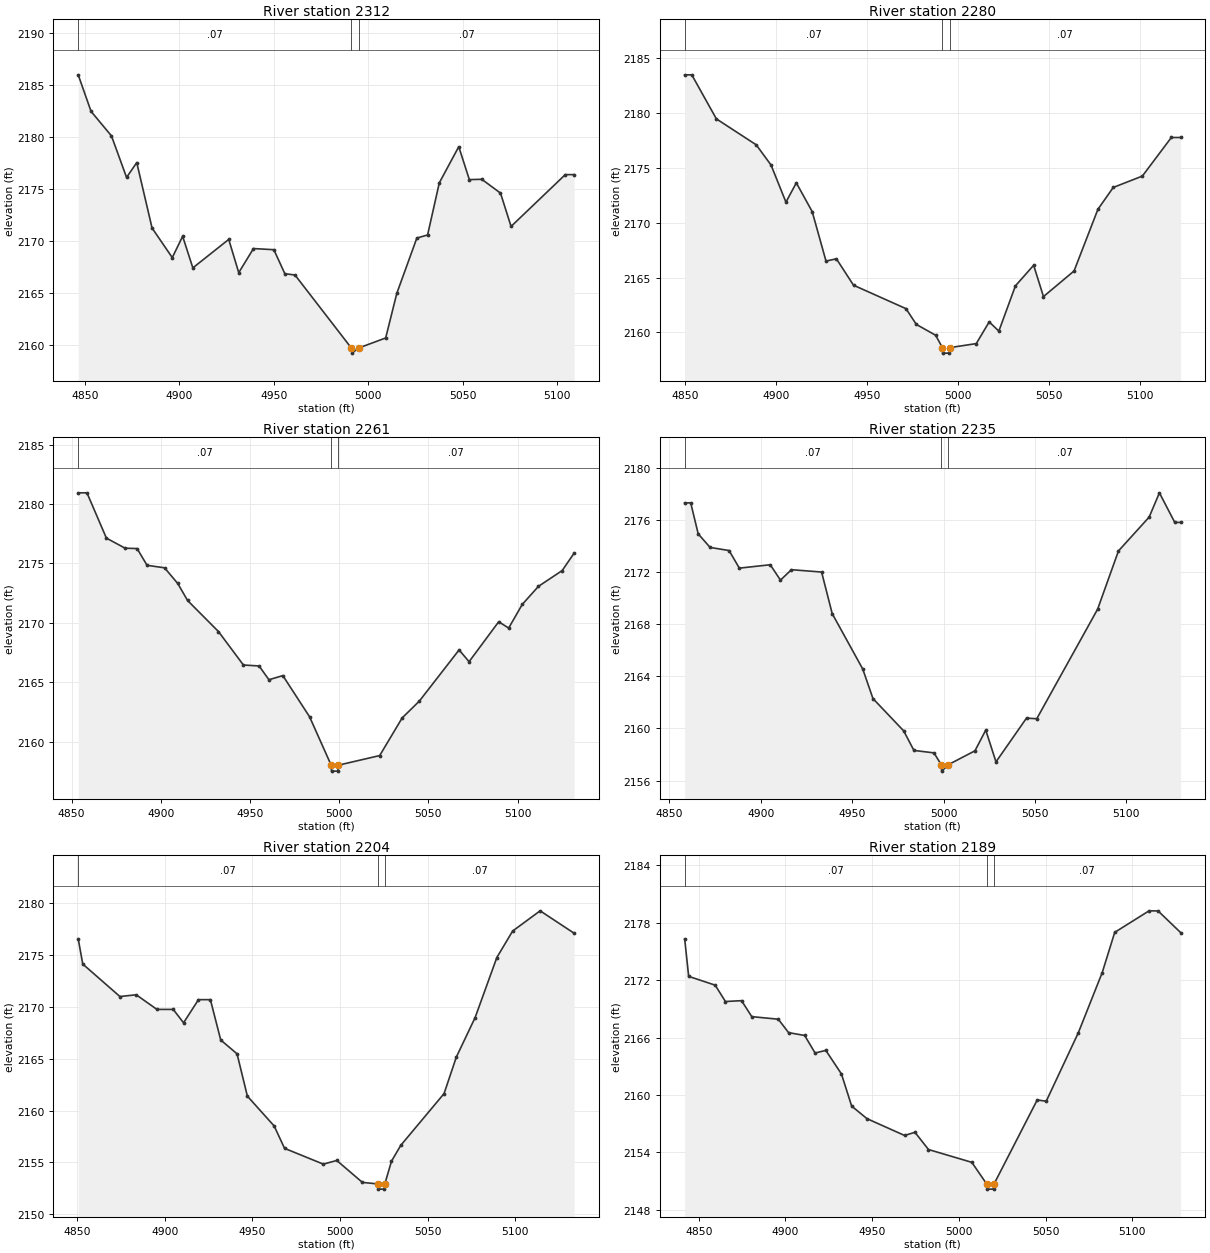
Type RM Length L Ch R = 1,2312,32,32,32
BEGIN DESCRIPTION:
Elm 61 2312.44
END DESCRIPTION:
XS GIS Cut Line= 3
      1521189.62      6768784.33      1521247.11      6768638.98
      1521295.94      6768544.57
#Sta/Elev= 30
  4846.5 2186.00  4853.3 2182.48  4864.1 2180.12  4872.1 2176.12  4877.5 2177.55
  4885.6 2171.25  4896.3 2168.40  4901.8 2170.45  4907.2 2167.41  4926.2 2170.15
  4931.5 2166.95  4939.3 2169.27  4950.1 2169.16  4955.9 2166.85  4961.3 2166.72
  4991.1 2159.70  4991.4 2159.20  4995.1 2159.70  5009.3 2160.66  5015.2 2164.96
  5025.8 2170.28  5031.5 2170.58  5037.7 2175.60  5048.0 2179.08  5053.6 2175.91
  5060.2 2175.94  5070.1 2174.61  5075.7 2171.40  5104.4 2176.39  5109.1 2176.39
#Mann=3,-1,0
  4846.5    0.07       0  4991.1    0.07       0  4995.1    0.07       0
Bank Sta=4991.1,4995.1
Exp/Cntr=0.3,0.1

Type RM Length L Ch R = 1,2280,19,19,19
BEGIN DESCRIPTION:
Elm 61 2280.28
END DESCRIPTION:
XS GIS Cut Line= 3
      1521202.62      6768789.81      1521273.16      6768657.42
      1521317.64      6768543.51
#Sta/Elev= 30
  4849.9 2183.50  4853.8 2183.50  4867.3 2179.48  4889.2 2177.11  4897.3 2175.27
  4905.5 2171.88  4911.2 2173.64  4919.9 2171.02  4927.5 2166.50  4933.2 2166.71
  4942.6 2164.30  4971.4 2162.16  4977.1 2160.72  4987.7 2159.73  4991.4 2158.60
  4991.6 2158.10  4995.1 2158.10  4995.4 2158.60  5010.0 2158.97  5017.1 2160.95
  5022.4 2160.11  5031.5 2164.24  5041.5 2166.12  5046.9 2163.26  5063.7 2165.60
  5076.8 2171.23  5085.2 2173.22  5101.2 2174.26  5117.1 2177.78  5122.2 2177.78
#Mann=3,-1,0
  4849.9    0.07       0  4991.4    0.07       0  4995.4    0.07       0
Bank Sta=4991.4,4995.4
Exp/Cntr=0.3,0.1

Type RM Length L Ch R = 1,2261,26,26,26
BEGIN DESCRIPTION:
Elm 61 2261.33
END DESCRIPTION:
XS GIS Cut Line= 3
      1521225.40      6768801.77      1521287.26      6768670.44
      1521347.53      6768552.06
#Sta/Elev= 30
  4853.7 2180.94  4858.6 2180.94  4869.5 2177.13  4880.0 2176.28  4886.7 2176.25
  4892.3 2174.84  4902.1 2174.63  4909.5 2173.31  4915.0 2171.88  4932.3 2169.27
  4946.3 2166.45  4955.1 2166.37  4960.6 2165.21  4968.4 2165.56  4983.4 2162.09
  4995.5 2158.02  4995.7 2157.52  4999.2 2157.52  4999.5 2158.02  5022.7 2158.83
  5035.3 2162.00  5044.9 2163.41  5067.2 2167.72  5072.8 2166.73  5089.4 2170.09
  5095.0 2169.56  5102.6 2171.55  5111.7 2173.07  5125.0 2174.40  5131.7 2175.87
#Mann=3,-1,0
  4853.7    0.07       0  4995.5    0.07       0  4999.5    0.07       0
Bank Sta=4995.5,4999.5
Exp/Cntr=0.3,0.1

Type RM Length L Ch R = 1,2235,31,31,31
BEGIN DESCRIPTION:
Elm 61 2234.89
END DESCRIPTION:
XS GIS Cut Line= 3
      1521247.10      6768810.45      1521310.05      6768682.38
      1521367.56      6768567.36
#Sta/Elev= 30
  4858.4 2177.31  4861.7 2177.31  4865.8 2174.93  4872.3 2173.89  4882.7 2173.65
  4888.3 2172.30  4905.2 2172.56  4910.8 2171.38  4916.8 2172.18  4933.3 2172.00
  4939.1 2168.81  4955.8 2164.56  4961.4 2162.29  4978.2 2159.81  4983.8 2158.31
  4994.8 2158.12  4998.7 2157.22  4999.0 2156.72  5002.7 2157.22  5017.2 2158.28
  5023.1 2159.87  5028.7 2157.43  5045.4 2160.79  5051.0 2160.74  5084.3 2169.15
  5095.7 2173.62  5112.5 2176.22  5118.1 2178.08  5126.5 2175.81  5129.7 2175.81
#Mann=3,-1,0
  4858.4    0.07       0  4998.7    0.07       0  5002.7    0.07       0
Bank Sta=4998.7,5002.7
Exp/Cntr=0.3,0.1

Type RM Length L Ch R = 1,2204,15,15,15
BEGIN DESCRIPTION:
Elm 61 2204.37
END DESCRIPTION:
XS GIS Cut Line= 3
      1521259.04      6768815.87      1521339.35      6768689.97
      1521387.08      6768565.22
#Sta/Elev= 30
  4850.6 2176.55  4853.2 2174.12  4874.4 2170.99  4883.7 2171.16  4895.5 2169.75
  4904.8 2169.75  4910.7 2168.46  4919.2 2170.69  4926.0 2170.69  4931.9 2166.80
  4941.2 2165.47  4947.1 2161.39  4962.4 2158.51  4968.3 2156.36  4990.4 2154.84
  4998.1 2155.19  5012.7 2153.08  5021.5 2152.93  5021.7 2152.43  5025.2 2152.43
  5025.5 2152.93  5029.3 2155.12  5034.6 2156.65  5059.3 2161.64  5066.3 2165.16
  5077.0 2168.96  5089.4 2174.75  5098.4 2177.30  5114.1 2179.25  5133.5 2177.09
#Mann=3,-1,0
  4850.6    0.07       0  5021.5    0.07       0  5025.5    0.07       0
Bank Sta=5021.5,5025.5
Exp/Cntr=0.3,0.1

Type RM Length L Ch R = 1,2189,31,31,31
BEGIN DESCRIPTION:
Elm 61 2188.75
END DESCRIPTION:
XS GIS Cut Line= 3
      1521269.89      6768826.72      1521356.71      6768689.97
      1521394.31      6768571.79
#Sta/Elev= 30
  4841.9 2176.32  4844.2 2172.40  4859.5 2171.48  4865.4 2169.77  4874.7 2169.86
  4880.6 2168.19  4895.9 2167.92  4901.8 2166.52  4911.1 2166.22  4917.1 2164.39
  4923.3 2164.66  4932.3 2162.20  4938.2 2158.84  4947.0 2157.53  4968.7 2155.77
  4974.7 2156.10  4982.5 2154.30  5007.5 2152.96  5016.2 2150.66  5016.5 2150.16
  5020.0 2150.16  5020.2 2150.66  5045.2 2159.48  5050.4 2159.35  5068.9 2166.50
  5082.7 2172.80  5089.9 2177.00  5109.7 2179.25  5114.9 2179.24  5127.9 2176.98
#Mann=3,-1,0
  4841.9    0.07       0  5016.2    0.07       0  5020.2    0.07       0
Bank Sta=5016.2,5020.2
Exp/Cntr=0.3,0.1

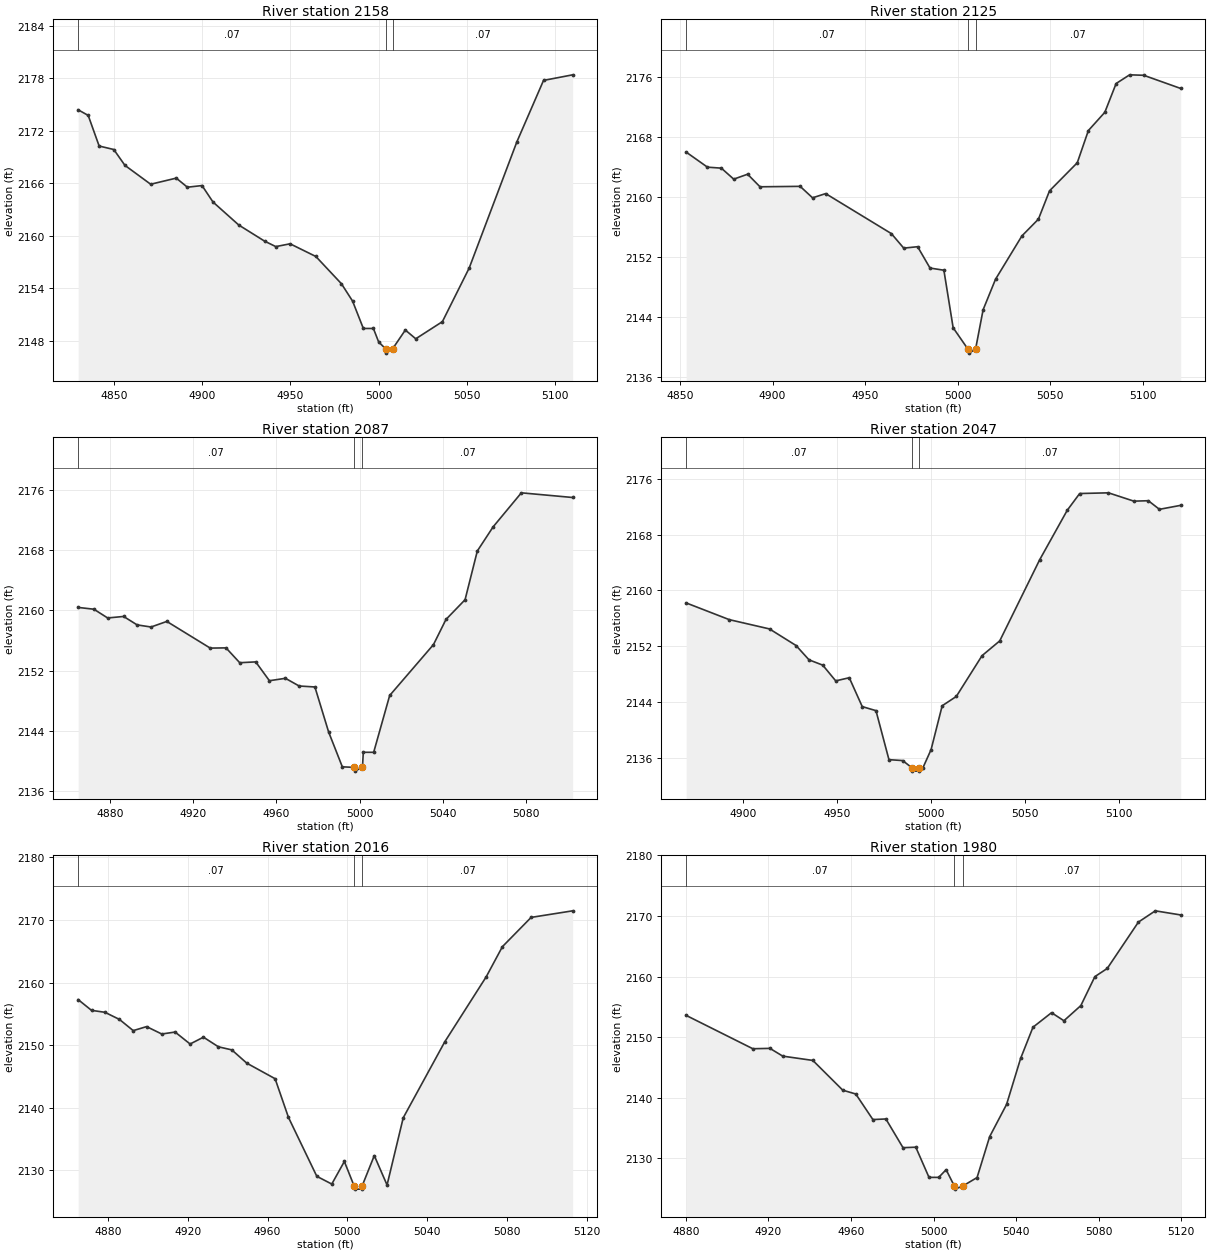
Type RM Length L Ch R = 1,2158,33,33,33
BEGIN DESCRIPTION:
Elm 61 2158.15
END DESCRIPTION:
XS GIS Cut Line= 3
      1521276.41      6768847.31      1521377.32      6768713.85
      1521439.18      6768619.43
#Sta/Elev= 30
  4829.8 2174.40  4835.5 2173.76  4841.7 2170.26  4850.0 2169.86  4856.3 2168.05
  4870.9 2165.89  4885.4 2166.59  4891.7 2165.55  4900.0 2165.74  4906.2 2163.86
  4920.8 2161.23  4935.4 2159.39  4941.8 2158.76  4949.9 2159.08  4964.5 2157.63
  4979.0 2154.51  4985.3 2152.53  4991.4 2149.40  4997.1 2149.40  5000.1 2147.85
  5004.0 2147.08  5004.3 2146.58  5008.0 2147.08  5015.2 2149.22  5021.1 2148.22
  5036.2 2150.18  5051.4 2156.32  5078.4 2170.74  5093.5 2177.76  5110.0 2178.40
#Mann=3,-1,0
  4829.8    0.07       0  5004.0    0.07       0  5008.0    0.07       0
Bank Sta=5004,5008
Exp/Cntr=0.3,0.1

Type RM Length L Ch R = 1,2125,38,38,38
BEGIN DESCRIPTION:
Elm 61 2124.7
END DESCRIPTION:
XS GIS Cut Line= 3
      1521304.61      6768844.07      1521402.28      6768735.55
      1521470.31      6768635.13
#Sta/Elev= 30
  4853.3 2166.02  4864.8 2164.01  4872.3 2163.88  4879.0 2162.41  4886.5 2163.07
  4893.2 2161.39  4914.9 2161.45  4921.6 2159.92  4928.7 2160.48  4964.2 2155.14
  4970.9 2153.20  4978.4 2153.39  4985.1 2150.54  4992.6 2150.25  4997.6 2142.57
  5005.7 2139.68  5006.0 2139.18  5009.7 2139.68  5013.8 2144.97  5020.5 2149.04
  5034.8 2154.84  5043.7 2157.07  5049.7 2160.85  5064.7 2164.60  5070.7 2168.90
  5079.6 2171.34  5085.7 2175.18  5093.0 2176.34  5100.6 2176.28  5120.6 2174.52
#Mann=3,-1,0
  4853.3    0.07       0  5005.7    0.07       0  5009.7    0.07       0
Bank Sta=5005.7,5009.7
Exp/Cntr=0.3,0.1

Type RM Length L Ch R = 1,2087,40,40,40
BEGIN DESCRIPTION:
Elm 61 2086.74
END DESCRIPTION:
XS GIS Cut Line= 3
      1521341.54      6768864.64      1521431.58      6768759.42
      1521485.83      6768675.87
#Sta/Elev= 30
  4864.5 2160.39  4872.1 2160.15  4878.7 2158.99  4886.4 2159.19  4892.9 2158.07
  4899.6 2157.79  4907.2 2158.53  4928.1 2154.99  4935.7 2155.02  4942.3 2153.05
  4950.0 2153.16  4956.6 2150.66  4964.3 2150.98  4970.9 2149.96  4978.5 2149.83
  4985.1 2143.86  4991.7 2139.23  4997.4 2139.16  4997.7 2138.66  5001.4 2139.16
  5001.8 2141.16  5006.8 2141.16  5014.5 2148.70  5035.6 2155.46  5041.6 2158.79
  5050.8 2161.41  5056.7 2167.88  5064.3 2171.08  5077.9 2175.60  5102.6 2174.98
#Mann=3,-1,0
  4864.5    0.07       0  4997.4    0.07       0  5001.4    0.07       0
Bank Sta=4997.4,5001.4
Exp/Cntr=0.3,0.1

Type RM Length L Ch R = 1,2047,31,31,31
BEGIN DESCRIPTION:
Elm 61 2047.26
END DESCRIPTION:
XS GIS Cut Line= 3
      1521368.64      6768884.20      1521455.45      6768793.06
      1521528.17      6768676.91
#Sta/Elev= 30
  4869.9 2158.22  4892.8 2155.83  4914.2 2154.50  4928.3 2152.13  4935.2 2150.08
  4942.5 2149.32  4949.4 2147.07  4956.6 2147.52  4963.5 2143.39  4970.8 2142.81
  4977.7 2135.80  4985.0 2135.67  4989.8 2134.66  4990.1 2134.16  4993.6 2134.16
  4993.8 2134.66  4995.8 2134.66  5000.1 2137.24  5006.0 2143.51  5013.5 2144.84
  5027.2 2150.68  5036.6 2152.79  5057.8 2164.38  5072.5 2171.48  5079.1 2173.87
  5094.4 2173.97  5107.9 2172.78  5115.6 2172.84  5121.5 2171.61  5132.8 2172.18
#Mann=3,-1,0
  4869.9    0.07       0  4989.8    0.07       0  4993.8    0.07       0
Bank Sta=4989.8,4993.8
Exp/Cntr=0.3,0.1

Type RM Length L Ch R = 1,2016,36,36,36
BEGIN DESCRIPTION:
Elm 61 2015.76
END DESCRIPTION:
XS GIS Cut Line= 3
      1521379.52      6768901.53      1521479.32      6768812.59
      1521549.96      6768722.96
#Sta/Elev= 30
  4865.1 2157.27  4871.8 2155.55  4878.5 2155.24  4885.8 2154.10  4892.7 2152.31
  4899.4 2152.95  4907.0 2151.77  4913.7 2152.08  4921.2 2150.17  4927.9 2151.26
  4935.4 2149.72  4942.1 2149.23  4949.6 2147.11  4963.8 2144.62  4970.5 2138.43
  4984.7 2129.02  4992.2 2127.78  4998.5 2131.39  5003.4 2127.47  5003.7 2126.97
  5007.2 2126.97  5007.4 2127.47  5013.5 2132.33  5019.9 2127.63  5028.0 2138.37
  5048.8 2150.51  5069.6 2160.92  5077.7 2165.73  5092.1 2170.41  5112.9 2171.46
#Mann=3,-1,0
  4865.1    0.07       0  5003.4    0.07       0  5007.4    0.07       0
Bank Sta=5003.4,5007.4
Exp/Cntr=0.3,0.1

Type RM Length L Ch R = 1,1980,22,22,22
BEGIN DESCRIPTION:
Elm 61 1979.9
END DESCRIPTION:
XS GIS Cut Line= 3
      1521409.89      6768909.15      1521507.53      6768835.37
      1521572.61      6768737.75
#Sta/Elev= 30
  4880.1 2153.58  4912.4 2148.08  4920.7 2148.14  4926.9 2146.86  4941.5 2146.15
  4956.0 2141.24  4962.3 2140.61  4970.6 2136.39  4976.9 2136.49  4985.2 2131.75
  4991.4 2131.83  4997.8 2126.85  5002.5 2126.85  5006.1 2128.12  5010.1 2125.41
  5010.4 2124.91  5014.1 2125.41  5021.1 2126.82  5027.2 2133.57  5035.4 2138.89
  5042.2 2146.47  5048.2 2151.63  5057.2 2154.03  5063.2 2152.70  5071.4 2155.20
  5078.2 2159.98  5084.2 2161.33  5099.3 2168.98  5107.5 2170.84  5119.8 2170.16
#Mann=3,-1,0
  4880.1    0.07       0  5010.1    0.07       0  5014.1    0.07       0
Bank Sta=5010.1,5014.1
Exp/Cntr=0.3,0.1

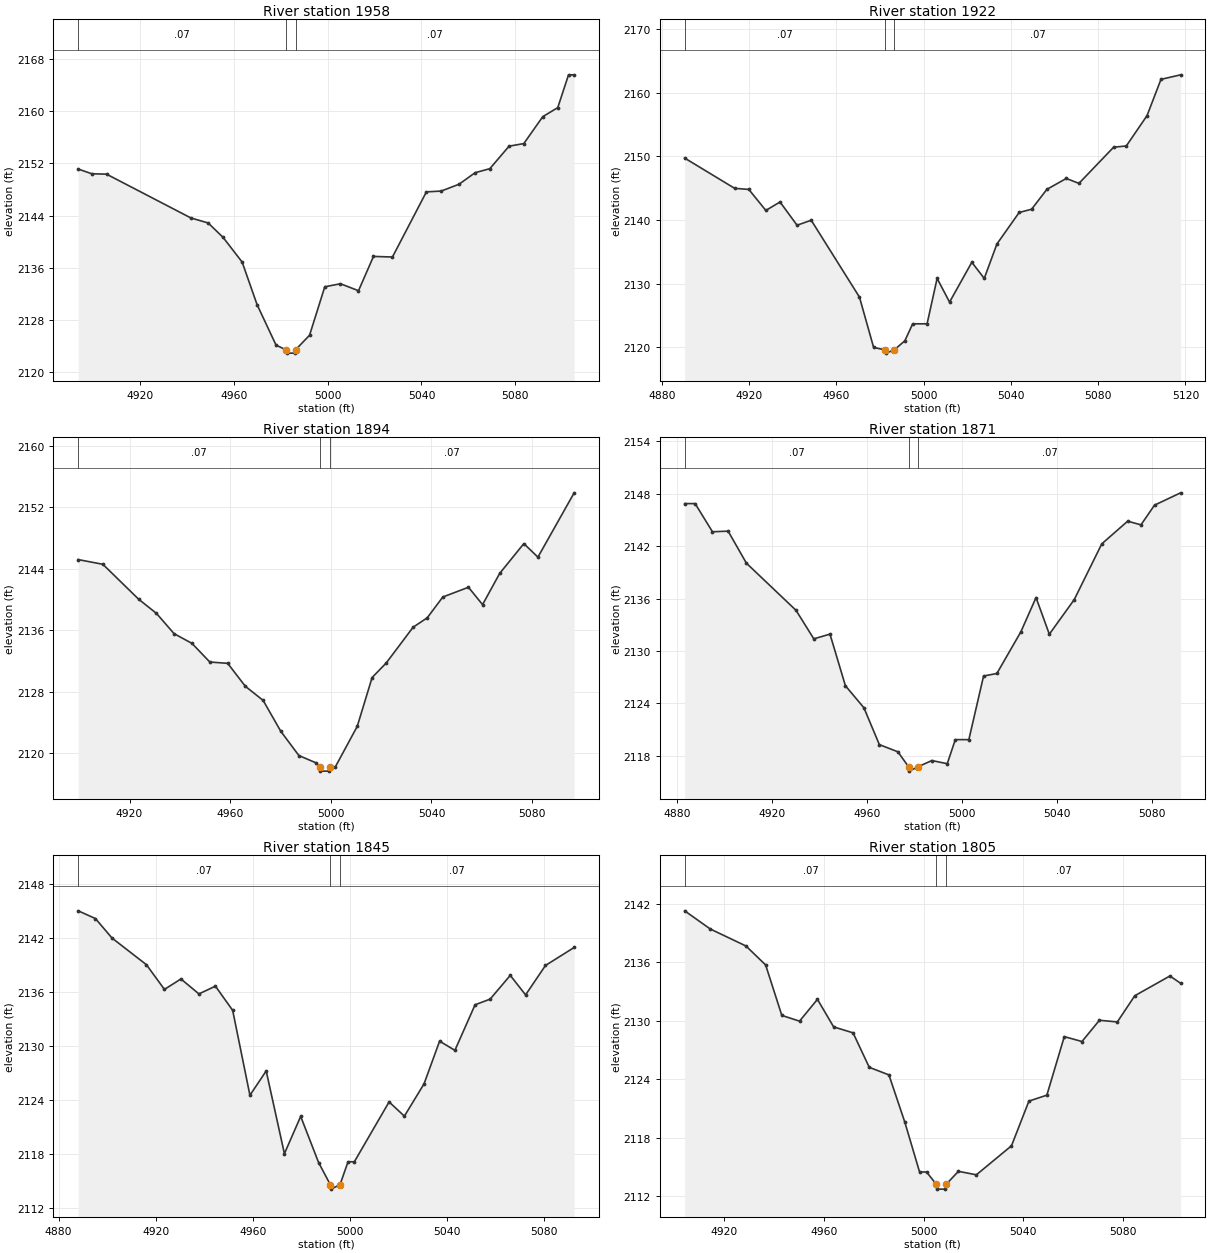
Type RM Length L Ch R = 1,1958,36,36,36
BEGIN DESCRIPTION:
Elm 61 1958.16
END DESCRIPTION:
XS GIS Cut Line= 3
      1521437.04      6768917.81      1521520.55      6768852.73
      1521585.66      6768769.18
#Sta/Elev= 30
  4893.4 2151.12  4899.2 2150.40  4905.5 2150.34  4941.5 2143.64  4948.9 2142.87
  4955.3 2140.65  4963.4 2136.89  4969.8 2130.36  4977.9 2124.17  4982.2 2123.45
  4982.5 2122.95  4986.0 2122.95  4986.2 2123.45  4992.2 2125.69  4998.7 2133.10
  5005.4 2133.57  5013.1 2132.50  5019.5 2137.75  5027.6 2137.66  5042.1 2147.63
  5048.4 2147.75  5056.0 2148.79  5062.9 2150.56  5069.2 2151.18  5077.4 2154.62
  5083.7 2155.02  5091.8 2159.14  5098.2 2160.52  5102.8 2165.54  5105.2 2165.54
#Mann=3,-1,0
  4893.4    0.07       0  4982.2    0.07       0  4986.2    0.07       0
Bank Sta=4982.2,4986.2
Exp/Cntr=0.3,0.1

Type RM Length L Ch R = 1,1922,28,28,28
BEGIN DESCRIPTION:
Elm 61 1922.48
END DESCRIPTION:
XS GIS Cut Line= 3
      1521463.07      6768948.20      1521545.51      6768878.78
      1521604.11      6768774.60
#Sta/Elev= 30
  4890.5 2149.73  4913.4 2144.98  4919.9 2144.81  4927.7 2141.51  4934.2 2142.84
  4942.0 2139.19  4948.5 2139.97  4970.6 2127.91  4977.1 2120.00  4982.5 2119.61
  4982.8 2119.11  4986.5 2119.61  4991.4 2121.04  4995.0 2123.71  5001.6 2123.71
  5006.2 2130.84  5011.9 2127.12  5022.1 2133.37  5027.8 2130.84  5033.6 2136.24
  5043.8 2141.19  5049.5 2141.70  5056.5 2144.82  5065.4 2146.53  5071.2 2145.76
  5087.1 2151.44  5092.9 2151.63  5102.4 2156.39  5108.8 2162.09  5117.8 2162.80
#Mann=3,-1,0
  4890.5    0.07       0  4982.5    0.07       0  4986.5    0.07       0
Bank Sta=4982.5,4986.5
Exp/Cntr=0.3,0.1

Type RM Length L Ch R = 1,1894,23,23,23
BEGIN DESCRIPTION:
Elm 61 1894.24
END DESCRIPTION:
XS GIS Cut Line= 3
      1521501.04      6768957.97      1521571.55      6768888.54
      1521617.57      6768801.85
#Sta/Elev= 30
  4899.6 2145.18  4909.4 2144.57  4923.6 2140.03  4930.7 2138.18  4937.7 2135.54
  4944.8 2134.28  4951.9 2131.85  4959.0 2131.68  4966.0 2128.70  4973.1 2126.85
  4980.1 2122.84  4987.3 2119.68  4994.3 2118.70  4995.5 2118.15  4995.7 2117.65
  4999.2 2117.65  4999.5 2118.15  5001.7 2118.15  5010.5 2123.48  5016.4 2129.83
  5022.0 2131.72  5032.7 2136.38  5038.3 2137.60  5044.5 2140.31  5054.7 2141.58
  5060.3 2139.32  5067.1 2143.38  5076.7 2147.26  5082.3 2145.50  5096.7 2153.87
#Mann=3,-1,0
  4899.6    0.07       0  4995.5    0.07       0  4999.5    0.07       0
Bank Sta=4995.5,4999.5
Exp/Cntr=0.3,0.1

Type RM Length L Ch R = 1,1871,26,26,26
BEGIN DESCRIPTION:
Elm 61 1871.07
END DESCRIPTION:
XS GIS Cut Line= 3
      1521520.54      6768979.70      1521594.34      6768891.80
      1521637.73      6768808.27
#Sta/Elev= 30
  4883.3 2146.85  4887.7 2146.85  4895.0 2143.63  4901.6 2143.70  4909.3 2140.04
  4930.2 2134.65  4937.7 2131.39  4944.5 2131.93  4951.0 2126.03  4958.8 2123.51
  4965.3 2119.30  4973.1 2118.48  4977.6 2116.77  4977.9 2116.27  4981.6 2116.77
  4987.4 2117.48  4993.9 2117.12  4997.3 2119.87  5003.0 2119.87  5009.2 2127.14
  5014.8 2127.43  5024.9 2132.19  5031.3 2136.11  5036.9 2131.92  5047.4 2135.88
  5059.0 2142.25  5069.9 2144.84  5075.5 2144.42  5081.2 2146.67  5092.2 2148.08
#Mann=3,-1,0
  4883.3    0.07       0  4977.6    0.07       0  4981.6    0.07       0
Bank Sta=4977.6,4981.6
Exp/Cntr=0.3,0.1

Type RM Length L Ch R = 1,1845,40,40,40
BEGIN DESCRIPTION:
Elm 61 1845.17
END DESCRIPTION:
XS GIS Cut Line= 3
      1521542.28      6768985.08      1521617.12      6768902.65
      1521673.53      6768828.88
#Sta/Elev= 30
  4888.1 2145.04  4895.2 2144.18  4902.0 2142.02  4916.2 2139.05  4923.6 2136.31
  4930.4 2137.47  4937.8 2135.81  4944.6 2136.67  4951.7 2133.98  4958.8 2124.55
  4965.5 2127.25  4973.0 2118.06  4979.7 2122.20  4987.1 2117.06  4991.9 2114.62
  4992.2 2114.12  4995.9 2114.62  4999.2 2117.16  5001.8 2117.16  5016.1 2123.81
  5022.4 2122.23  5030.5 2125.82  5036.9 2130.56  5043.2 2129.54  5051.5 2134.60
  5057.7 2135.23  5066.0 2137.87  5072.3 2135.70  5080.5 2138.97  5092.3 2140.97
#Mann=3,-1,0
  4888.1    0.07       0  4991.9    0.07       0  4995.9    0.07       0
Bank Sta=4991.9,4995.9
Exp/Cntr=0.3,0.1

Type RM Length L Ch R = 1,1805,29,29,29
BEGIN DESCRIPTION:
Elm 61 1805.06
END DESCRIPTION:
XS GIS Cut Line= 3
      1521585.64      6769003.58      1521647.51      6768928.69
      1521720.67      6768857.67
#Sta/Elev= 30
  4904.1 2141.30  4914.4 2139.43  4928.7 2137.69  4936.6 2135.74  4943.1 2130.56
  4950.2 2129.97  4957.4 2132.21  4963.9 2129.38  4971.7 2128.77  4978.2 2125.23
  4986.1 2124.45  4992.5 2119.58  4998.4 2114.48  5001.2 2114.48  5005.1 2113.22
  5005.3 2112.72  5008.8 2112.72  5009.1 2113.22  5014.0 2114.55  5021.2 2114.19
  5035.3 2117.17  5042.3 2121.76  5049.5 2122.37  5056.5 2128.38  5063.6 2127.88
  5070.6 2130.06  5077.8 2129.89  5084.8 2132.58  5098.9 2134.61  5103.2 2133.86
#Mann=3,-1,0
  4904.1    0.07       0  5005.1    0.07       0  5009.1    0.07       0
Bank Sta=5005.1,5009.1
Exp/Cntr=0.3,0.1

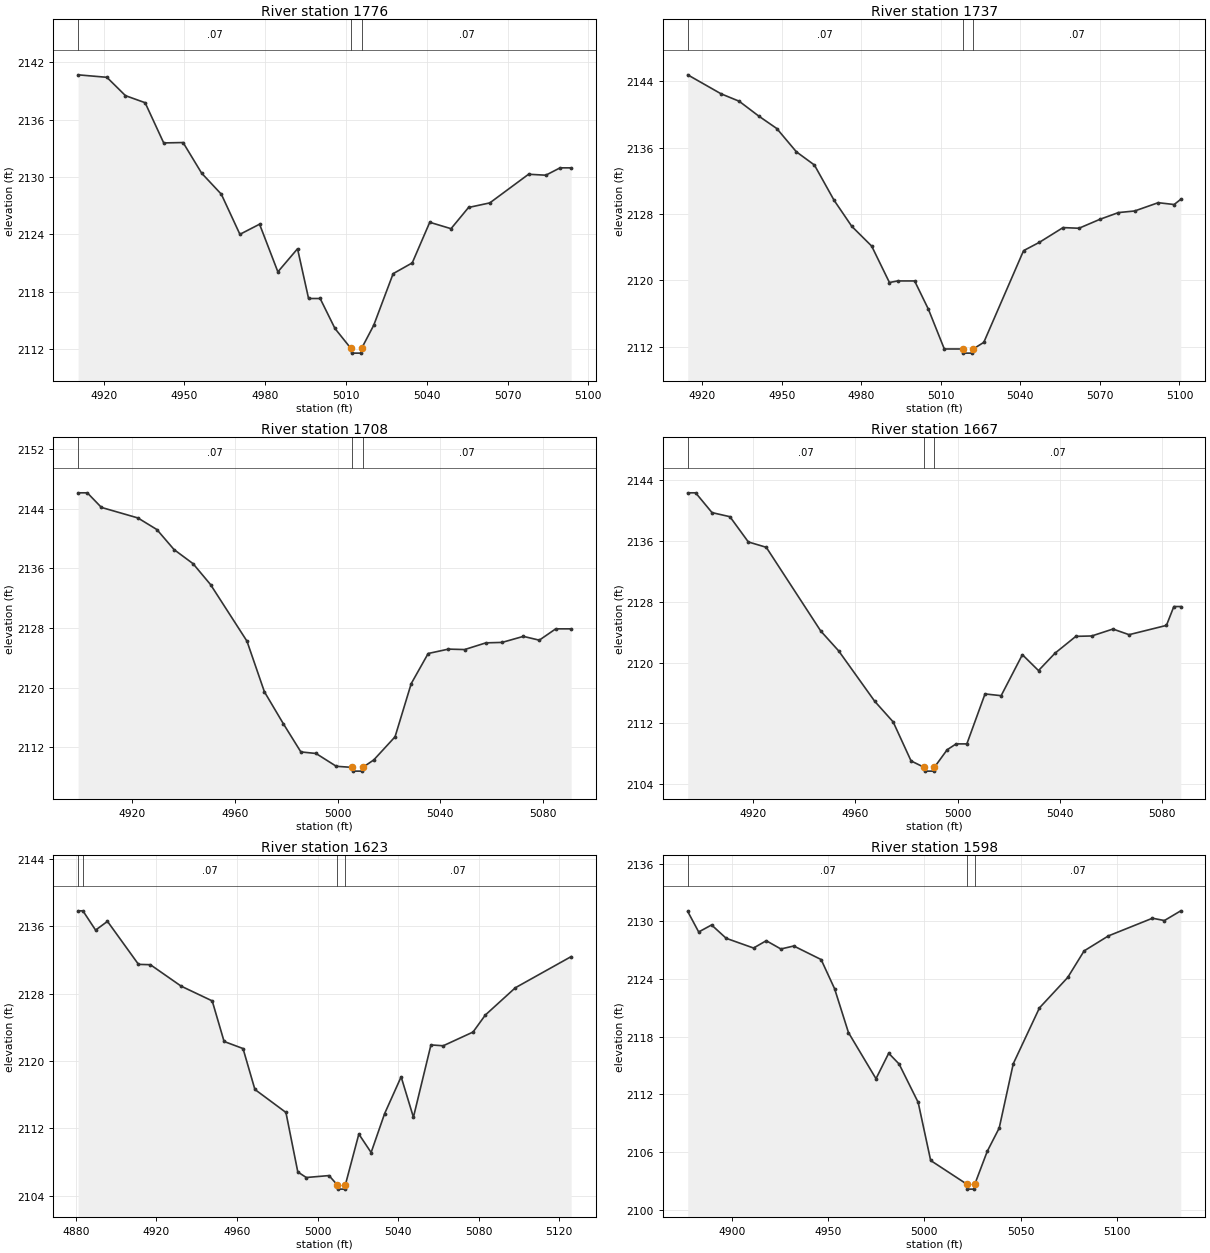
Type RM Length L Ch R = 1,1776,39,39,39
BEGIN DESCRIPTION:
Elm 61 1776.29
END DESCRIPTION:
XS GIS Cut Line= 3
      1521603.02      6769011.15      1521665.95      6768951.48
      1521726.69      6768876.64
#Sta/Elev= 30
  4910.5 2140.70  4921.2 2140.44  4928.1 2138.52  4935.4 2137.78  4942.3 2133.57
  4949.5 2133.61  4956.4 2130.40  4963.7 2128.20  4970.6 2124.00  4977.9 2125.06
  4984.7 2120.07  4992.0 2122.49  4996.1 2117.28  5000.4 2117.28  5005.9 2114.14
  5011.8 2112.06  5012.1 2111.56  5015.6 2111.56  5015.8 2112.06  5020.3 2114.48
  5027.5 2119.88  5034.6 2121.01  5041.1 2125.26  5049.0 2124.59  5055.5 2126.81
  5063.4 2127.29  5077.8 2130.29  5084.2 2130.19  5089.5 2130.96  5093.6 2130.96
#Mann=3,-1,0
  4910.5    0.07       0  5011.8    0.07       0  5015.8    0.07       0
Bank Sta=5011.8,5015.8
Exp/Cntr=0.3,0.1

Type RM Length L Ch R = 1,1737,29,29,29
BEGIN DESCRIPTION:
Elm 61 1737.46
END DESCRIPTION:
XS GIS Cut Line= 3
      1521638.81      6769039.38      1521694.16      6768978.60
      1521752.74      6768892.91
#Sta/Elev= 30
  4914.5 2144.78  4927.1 2142.49  4933.9 2141.60  4941.3 2139.81  4948.1 2138.31
  4955.5 2135.50  4962.3 2133.91  4969.7 2129.67  4976.4 2126.52  4983.9 2124.14
  4990.6 2119.75  4993.7 2119.94  5000.1 2119.94  5005.3 2116.53  5011.3 2111.74
  5018.2 2111.74  5018.4 2111.24  5021.9 2111.24  5022.2 2111.74  5026.2 2112.54
  5041.2 2123.59  5047.2 2124.60  5056.1 2126.37  5062.1 2126.29  5070.1 2127.38
  5077.0 2128.18  5083.1 2128.37  5092.0 2129.37  5098.0 2129.15  5100.5 2129.78
#Mann=3,-1,0
  4914.5    0.07       0  5018.2    0.07       0  5022.2    0.07       0
Bank Sta=5018.2,5022.2
Exp/Cntr=0.3,0.1

Type RM Length L Ch R = 1,1708,41,41,41
BEGIN DESCRIPTION:
Elm 61 1707.65
END DESCRIPTION:
XS GIS Cut Line= 3
      1521655.11      6769061.06      1521718.03      6768992.71
      1521777.72      6768913.49
#Sta/Elev= 30
  4898.9 2146.14  4902.5 2146.14  4908.0 2144.18  4922.2 2142.77  4929.6 2141.21
  4936.3 2138.52  4943.7 2136.63  4950.5 2133.83  4964.7 2126.23  4971.5 2119.43
  4978.9 2115.13  4985.7 2111.36  4991.6 2111.15  4999.5 2109.43  5005.8 2109.28
  5006.1 2108.78  5009.6 2108.78  5009.8 2109.28  5014.1 2110.28  5022.4 2113.39
  5028.7 2120.53  5035.3 2124.57  5043.2 2125.16  5049.5 2125.10  5057.8 2126.00
  5064.1 2126.06  5072.4 2126.87  5078.6 2126.36  5085.0 2127.88  5091.0 2127.88
#Mann=3,-1,0
  4898.9    0.07       0  5005.8    0.07       0  5009.8    0.07       0
Bank Sta=5005.8,5009.8
Exp/Cntr=0.3,0.1

Type RM Length L Ch R = 1,1667,44,44,44
BEGIN DESCRIPTION:
Elm 61 1666.7
END DESCRIPTION:
XS GIS Cut Line= 3
      1521685.48      6769071.92      1521761.44      6768998.13
      1521813.52      6768928.69
#Sta/Elev= 30
  4894.5 2142.31  4897.6 2142.31  4904.0 2139.71  4911.0 2139.17  4918.2 2135.85
  4925.2 2135.15  4946.5 2124.14  4953.5 2121.53  4967.6 2114.90  4974.8 2112.19
  4981.8 2107.06  4986.9 2106.22  4987.2 2105.72  4990.7 2105.72  4990.9 2106.22
  4995.9 2108.53  4999.4 2109.30  5003.6 2109.30  5010.7 2115.87  5017.0 2115.64
  5025.3 2121.03  5031.6 2118.94  5038.1 2121.24  5046.2 2123.44  5052.4 2123.49
  5060.7 2124.40  5067.0 2123.66  5081.6 2124.88  5084.5 2127.36  5087.2 2127.36
#Mann=3,-1,0
  4894.5    0.07       0  4986.9    0.07       0  4990.9    0.07       0
Bank Sta=4986.9,4990.9
Exp/Cntr=0.3,0.1

Type RM Length L Ch R = 1,1623,25,25,25
BEGIN DESCRIPTION:
Elm 61 1623.35
END DESCRIPTION:
XS GIS Cut Line= 3
      1521695.25      6769089.28      1521792.90      6769028.52
      1521867.11      6768922.04
#Sta/Elev= 30
  4881.1 2137.83  4883.5 2137.83  4889.8 2135.54  4895.7 2136.58  4911.1 2131.47
  4917.0 2131.43  4932.3 2128.88  4947.7 2127.13  4953.6 2122.31  4963.0 2121.47
  4968.9 2116.61  4984.3 2113.88  4990.2 2106.81  4994.4 2106.15  5005.7 2106.38
  5009.8 2105.27  5010.0 2104.77  5013.5 2104.77  5013.8 2105.27  5020.5 2111.31
  5026.6 2109.12  5033.3 2113.74  5041.5 2118.11  5047.6 2113.31  5056.3 2121.90
  5062.4 2121.80  5077.2 2123.43  5083.3 2125.45  5098.2 2128.69  5125.9 2132.39
#Mann=4,-1,0
  4881.1    0.16       0  4883.5    0.07       0  5009.8    0.07       0
  5013.8    0.07       0
Bank Sta=5009.8,5013.8
Exp/Cntr=0.3,0.1

Type RM Length L Ch R = 1,1598,29,29,29
BEGIN DESCRIPTION:
Elm 61 1597.94
END DESCRIPTION:
XS GIS Cut Line= 3
      1521727.76      6769118.61      1521810.27      6769045.88
      1521896.01      6768927.57
#Sta/Elev= 30
  4877.1 2131.05  4882.8 2128.91  4889.5 2129.64  4897.1 2128.25  4911.3 2127.24
  4917.9 2128.00  4925.5 2127.14  4932.2 2127.45  4946.4 2126.04  4953.4 2123.00
  4960.6 2118.44  4974.9 2113.64  4981.5 2116.29  4986.9 2115.17  4996.8 2111.18
  5003.3 2105.13  5022.2 2102.65  5022.4 2102.15  5025.9 2102.15  5026.2 2102.65
  5032.7 2106.09  5038.9 2108.51  5046.2 2115.20  5059.8 2121.01  5074.5 2124.18
  5083.0 2126.94  5095.6 2128.50  5118.5 2130.34  5124.7 2130.10  5133.2 2131.11
#Mann=3,-1,0
  4877.1    0.07       0  5022.2    0.07       0  5026.2    0.07       0
Bank Sta=5022.2,5026.2
Exp/Cntr=0.3,0.1