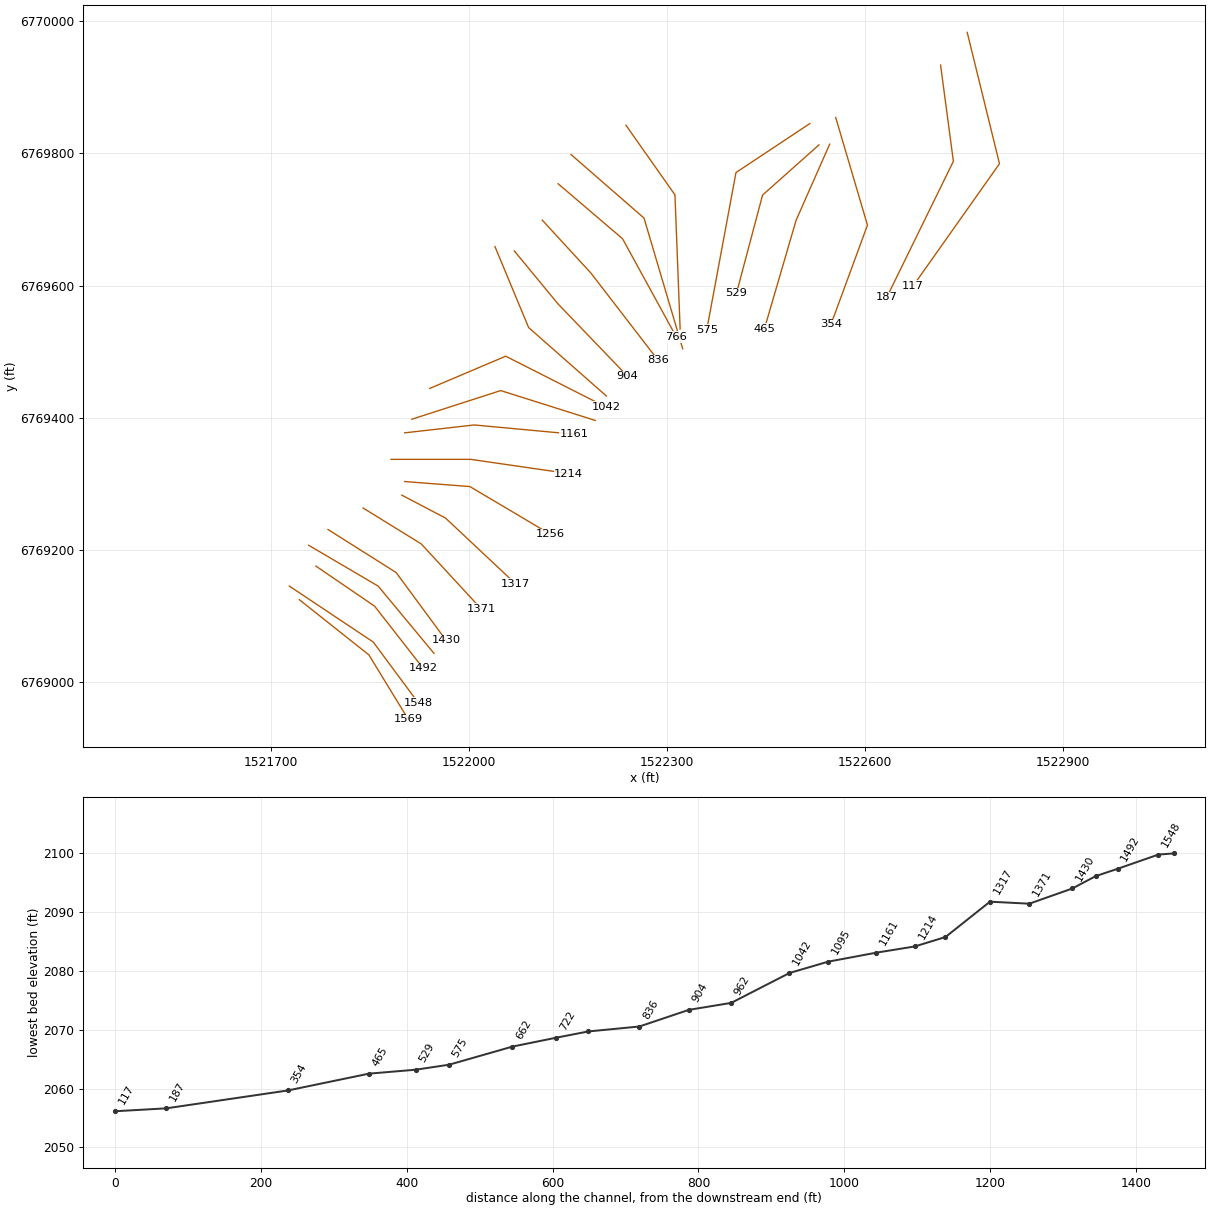
HEC-RAS study Elm 61.prj: Elm 61 Base Level Engineering

--- Elm 61.g01 (geometry) --- (continued)

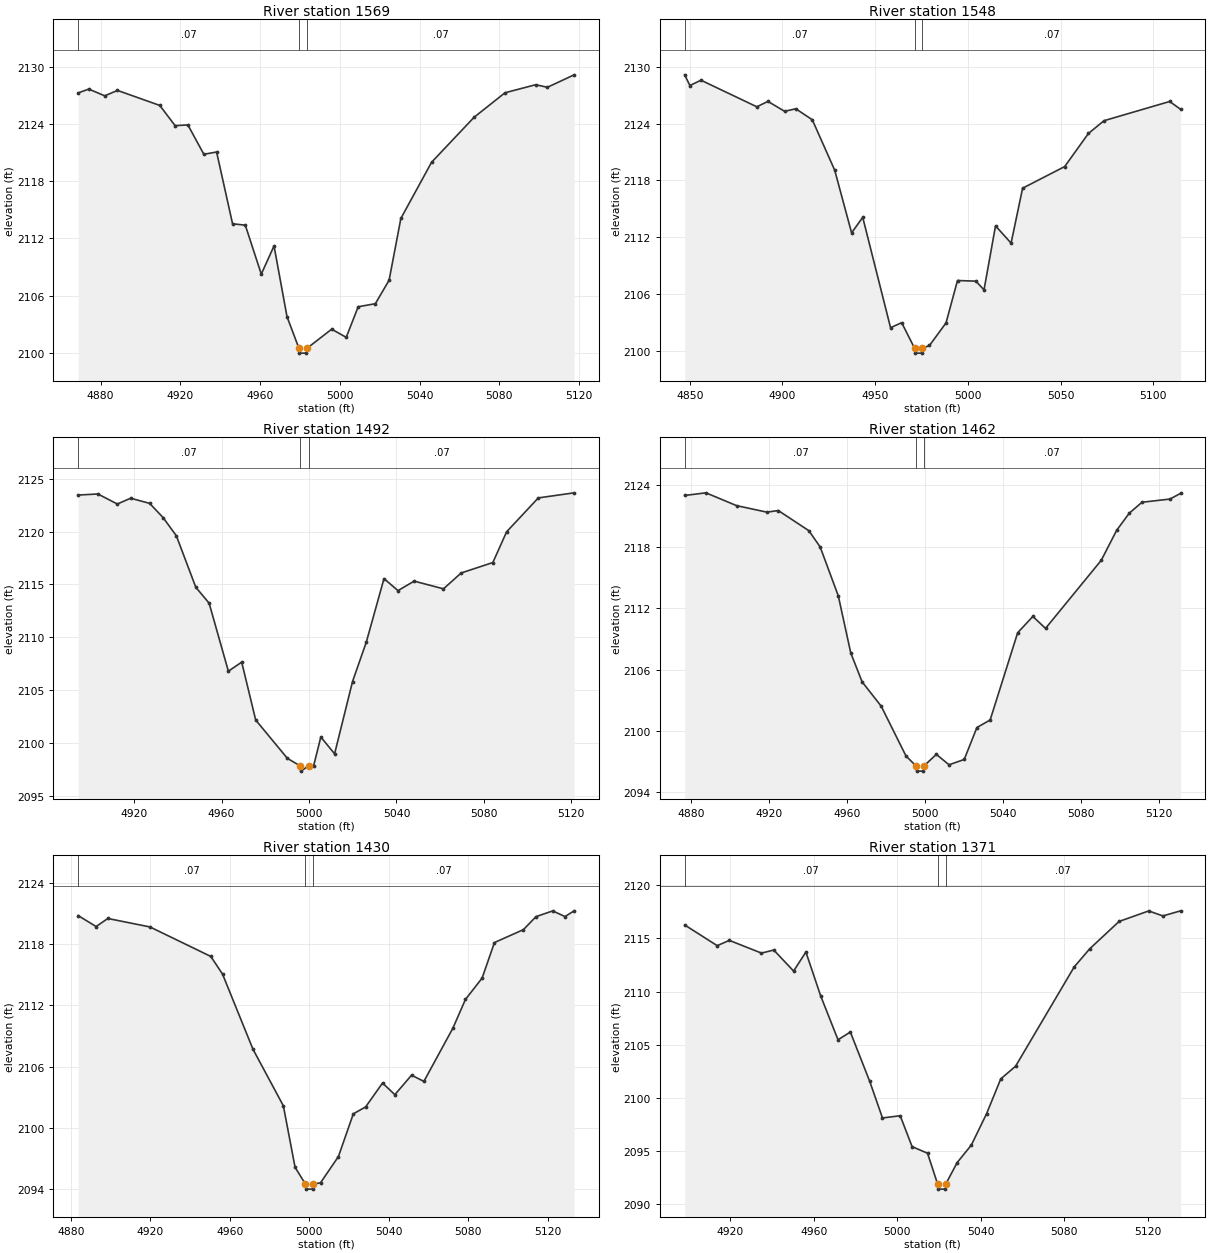
Type RM Length L Ch R = 1,1569,21,21,21
BEGIN DESCRIPTION:
Elm 61 1569.18
END DESCRIPTION:
XS GIS Cut Line= 3
      1521742.98      6769124.01      1521848.24      6769040.45
      1521907.85      6768942.91
#Sta/Elev= 30
  4868.8 2127.32  4874.1 2127.72  4882.1 2127.01  4888.5 2127.58  4909.7 2126.00
  4917.4 2123.87  4923.8 2123.95  4931.8 2120.86  4938.2 2121.10  4946.2 2113.55
  4952.6 2113.40  4960.6 2108.25  4967.0 2111.22  4973.5 2103.78  4979.5 2100.44
  4979.7 2099.94  4983.2 2099.94  4983.5 2100.44  4995.9 2102.46  5003.2 2101.60
  5009.2 2104.82  5017.8 2105.14  5024.7 2107.61  5030.6 2114.11  5046.0 2120.02
  5067.3 2124.75  5082.8 2127.33  5098.2 2128.18  5104.1 2127.91  5117.5 2129.22
#Mann=3,-1,0
  4868.8    0.07       0  4979.5    0.07       0  4983.5    0.07       0
Bank Sta=4979.5,4983.5
Exp/Cntr=0.3,0.1

Type RM Length L Ch R = 1,1548,56,56,56
BEGIN DESCRIPTION:
Elm 61 1547.73
END DESCRIPTION:
XS GIS Cut Line= 3
      1521727.76      6769144.65      1521854.75      6769059.98
      1521923.10      6768967.78
#Sta/Elev= 30
  4847.3 2129.17  4850.1 2128.04  4856.1 2128.60  4886.2 2125.79  4892.2 2126.36
  4901.2 2125.31  4907.2 2125.58  4916.1 2124.42  4928.2 2119.08  4937.3 2112.46
  4943.3 2114.10  4958.3 2102.43  4964.3 2102.96  4971.3 2100.24  4971.6 2099.74
  4975.1 2099.74  4975.3 2100.24  4979.3 2100.55  4988.2 2102.93  4994.4 2107.42
  5004.3 2107.35  5008.7 2106.43  5014.9 2113.20  5023.3 2111.37  5029.5 2117.18
  5052.2 2119.47  5065.0 2122.97  5073.4 2124.32  5108.8 2126.35  5114.7 2125.52
#Mann=3,-1,0
  4847.3    0.07       0  4971.3    0.07       0  4975.3    0.07       0
Bank Sta=4971.3,4975.3
Exp/Cntr=0.3,0.1

Type RM Length L Ch R = 1,1492,30,30,30
BEGIN DESCRIPTION:
Elm 61 1492.23
END DESCRIPTION:
XS GIS Cut Line= 3
      1521767.98      6769174.98      1521856.92      6769114.24
      1521930.32      6769020.33
#Sta/Elev= 30
  4894.4 2123.46  4903.4 2123.56  4912.3 2122.61  4918.4 2123.16  4927.1 2122.67
  4933.3 2121.31  4939.3 2119.60  4948.2 2114.73  4954.3 2113.22  4963.1 2106.78
  4969.2 2107.64  4975.6 2102.16  4990.1 2098.53  4995.9 2097.82  4996.2 2097.32
  4999.9 2097.82  5002.1 2097.82  5005.4 2100.55  5011.7 2098.96  5019.9 2105.80
  5026.2 2109.53  5034.3 2115.55  5040.7 2114.41  5048.1 2115.31  5061.5 2114.58
  5069.6 2116.08  5084.1 2117.07  5090.4 2119.98  5104.9 2123.19  5121.3 2123.67
#Mann=3,-1,0
  4894.4    0.07       0  4995.9    0.07       0  4999.9    0.07       0
Bank Sta=4995.9,4999.9
Exp/Cntr=0.3,0.1

Type RM Length L Ch R = 1,1462,32,32,32
BEGIN DESCRIPTION:
Elm 61 1462.49
END DESCRIPTION:
XS GIS Cut Line= 3
      1521757.10      6769206.46      1521862.35      6769144.62
      1521946.85      6769042.78
#Sta/Elev= 30
  4876.6 2123.02  4887.5 2123.28  4903.2 2122.03  4918.8 2121.39  4924.6 2121.55
  4940.3 2119.58  4946.1 2117.99  4955.4 2113.21  4961.8 2107.63  4967.6 2104.81
  4977.4 2102.43  4990.1 2097.57  4995.3 2096.58  4995.6 2096.08  4999.1 2096.08
  4999.3 2096.58  5005.7 2097.72  5012.2 2096.70  5020.0 2097.22  5026.5 2100.34
  5033.3 2101.08  5047.4 2109.60  5055.2 2111.20  5061.7 2110.03  5090.3 2116.69
  5098.2 2119.62  5104.7 2121.30  5111.2 2122.36  5125.5 2122.67  5131.0 2123.23
#Mann=3,-1,0
  4876.6    0.07       0  4995.3    0.07       0  4999.3    0.07       0
Bank Sta=4995.3,4999.3
Exp/Cntr=0.3,0.1

Type RM Length L Ch R = 1,1430,59,59,59
BEGIN DESCRIPTION:
Elm 61 1429.74
END DESCRIPTION:
XS GIS Cut Line= 3
      1521786.37      6769230.35      1521889.48      6769165.23
      1521965.14      6769062.55
#Sta/Elev= 30
  4883.7 2120.79  4892.7 2119.72  4898.6 2120.51  4919.8 2119.68  4950.4 2116.79
  4956.3 2115.06  4971.6 2107.70  4986.9 2102.15  4992.8 2096.12  4998.0 2094.48
  4998.3 2093.98  5001.8 2093.98  5002.0 2094.48  5005.6 2094.60  5014.6 2097.17
  5022.1 2101.36  5028.3 2102.04  5036.8 2104.38  5043.0 2103.24  5051.4 2105.15
  5057.6 2104.54  5072.2 2109.76  5078.5 2112.57  5086.9 2114.67  5093.1 2118.15
  5107.7 2119.42  5114.0 2120.69  5122.4 2121.25  5128.6 2120.70  5133.2 2121.26
#Mann=3,-1,0
  4883.7    0.07       0  4998.0    0.07       0  5002.0    0.07       0
Bank Sta=4998,5002
Exp/Cntr=0.3,0.1

Type RM Length L Ch R = 1,1371,54,54,54
BEGIN DESCRIPTION:
Elm 61 1371.27
END DESCRIPTION:
XS GIS Cut Line= 3
      1521839.56      6769262.89      1521927.45      6769208.64
      1522018.62      6769109.88
#Sta/Elev= 30
  4898.1 2116.27  4913.7 2114.32  4919.5 2114.82  4934.9 2113.62  4940.8 2113.91
  4950.3 2111.93  4956.2 2113.72  4963.3 2109.58  4971.6 2105.46  4977.5 2106.19
  4986.8 2101.54  4992.9 2098.10  5001.4 2098.31  5007.1 2095.40  5014.5 2094.78
  5019.3 2091.90  5019.5 2091.40  5023.0 2091.40  5023.3 2091.90  5028.7 2093.90
  5035.5 2095.55  5042.8 2098.50  5049.6 2101.78  5056.7 2102.97  5084.8 2112.32
  5092.2 2114.02  5106.3 2116.60  5120.5 2117.59  5127.3 2117.12  5135.8 2117.60
#Mann=3,-1,0
  4898.1    0.07       0  5019.3    0.07       0  5023.3    0.07       0
Bank Sta=5019.3,5023.3
Exp/Cntr=0.3,0.1

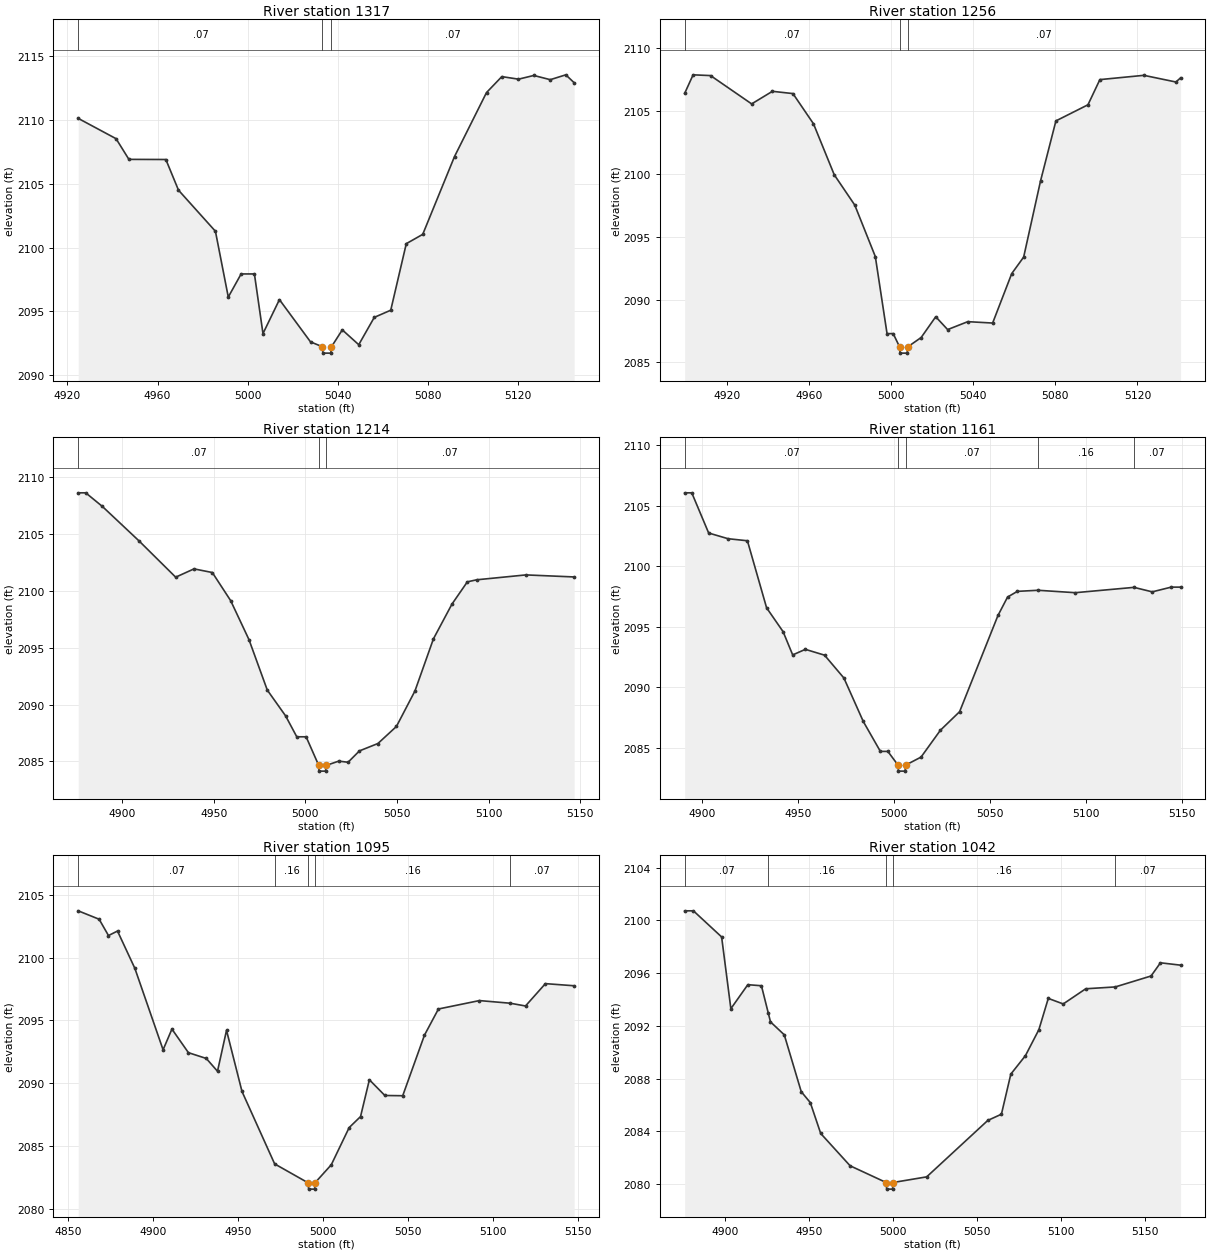
Type RM Length L Ch R = 1,1317,61,61,61
BEGIN DESCRIPTION:
Elm 61 1317.22
END DESCRIPTION:
XS GIS Cut Line= 3
      1521898.17      6769282.42      1521964.35      6769247.70
      1522070.33      6769148.21
#Sta/Elev= 30
  4924.8 2110.12  4941.6 2108.53  4947.3 2106.91  4963.7 2106.90  4969.3 2104.50
  4985.7 2101.28  4991.4 2096.13  4997.1 2097.94  5003.0 2097.94  5006.8 2093.27
  5014.1 2095.93  5027.9 2092.62  5033.2 2092.24  5033.4 2091.74  5036.9 2091.74
  5037.2 2092.24  5042.0 2093.56  5049.3 2092.40  5056.2 2094.54  5063.5 2095.10
  5070.4 2100.31  5077.7 2101.04  5091.8 2107.13  5106.0 2112.14  5112.8 2113.39
  5120.2 2113.19  5127.0 2113.48  5134.3 2113.15  5141.2 2113.53  5144.9 2112.91
#Mann=3,-1,0
  4924.8    0.07       0  5033.2    0.07       0  5037.2    0.07       0
Bank Sta=5033.2,5037.2
Exp/Cntr=0.3,0.1

Type RM Length L Ch R = 1,1256,42,42,42
BEGIN DESCRIPTION:
Elm 61 1255.83
END DESCRIPTION:
XS GIS Cut Line= 3
      1521902.46      6769303.04      1522001.24      6769295.44
      1522123.66      6769222.85
#Sta/Elev= 30
  4899.6 2106.38  4903.7 2107.85  4912.2 2107.79  4932.2 2105.54  4942.3 2106.54
  4952.3 2106.36  4962.3 2103.96  4972.4 2099.91  4982.4 2097.50  4992.4 2093.41
  4998.1 2087.29  5001.1 2087.29  5004.2 2086.24  5004.4 2085.74  5007.9 2085.74
  5008.2 2086.24  5014.7 2086.98  5021.8 2088.63  5027.6 2087.61  5037.4 2088.24
  5049.5 2088.13  5058.8 2092.06  5064.6 2093.37  5072.8 2099.41  5080.3 2104.19
  5095.9 2105.47  5101.7 2107.47  5123.1 2107.81  5138.7 2107.28  5141.0 2107.61
#Mann=3,-1,0
  4899.6    0.07       0  5004.2    0.07       0  5008.2    0.07       0
Bank Sta=5004.2,5008.2
Exp/Cntr=0.3,0.1

Type RM Length L Ch R = 1,1214,53,53,53
BEGIN DESCRIPTION:
Elm 61 1214.18
END DESCRIPTION:
XS GIS Cut Line= 3
      1521881.85      6769336.68      1522002.32      6769336.68
      1522150.99      6769315.13
#Sta/Elev= 29
  4876.0 2108.62  4880.1 2108.62  4889.2 2107.42  4909.2 2104.39  4929.2 2101.20
  4939.2 2101.93  4949.2 2101.61  4959.2 2099.14  4969.2 2095.71  4979.2 2091.27
  4989.2 2089.00  4995.3 2087.16  5000.4 2087.16  5007.3 2084.64  5007.5 2084.14
  5011.0 2084.14  5011.3 2084.64  5018.2 2085.02  5023.3 2084.92  5029.5 2085.92
  5039.6 2086.57  5049.7 2088.07  5059.8 2091.19  5069.9 2095.78  5080.0 2098.83
  5088.4 2100.79  5093.5 2100.97  5120.4 2101.40  5146.7 2101.22
#Mann=3,-1,0
  4876.0    0.07       0  5007.3    0.07       0  5011.3    0.07       0
Bank Sta=5007.3,5011.3
Exp/Cntr=0.3,0.1

Type RM Length L Ch R = 1,1161,66,66,66
BEGIN DESCRIPTION:
Elm 61 1160.96
END DESCRIPTION:
XS GIS Cut Line= 3
      1521902.53      6769376.83      1522007.75      6769388.76
      1522159.70      6769374.65
#Sta/Elev= 30
  4891.0 2106.07  4894.7 2106.07  4903.5 2102.75  4913.6 2102.28  4923.7 2102.11
  4933.7 2096.57  4942.3 2094.60  4947.3 2092.68  4953.9 2093.14  4963.9 2092.66
  4974.0 2090.77  4984.1 2087.18  4993.0 2084.71  4996.9 2084.71  5002.2 2083.58
  5002.4 2083.08  5005.9 2083.08  5006.2 2083.58  5014.2 2084.24  5024.3 2086.46
  5034.3 2087.99  5054.3 2095.94  5059.3 2097.46  5064.4 2097.93  5075.2 2098.02
  5094.6 2097.82  5125.2 2098.26  5134.7 2097.89  5144.6 2098.28  5149.5 2098.28
#Mann=5,-1,0
  4891.0    0.07       0  5002.2    0.07       0  5006.2    0.07       0
  5075.2    0.16       0  5125.2    0.07       0
Bank Sta=5002.2,5006.2
Exp/Cntr=0.3,0.1

Type RM Length L Ch R = 1,1095,53,53,53
BEGIN DESCRIPTION:
Elm 61 1095.41
END DESCRIPTION:
XS GIS Cut Line= 3
      1521913.33      6769397.43      1522047.90      6769440.84
      1522191.13      6769395.61
#Sta/Elev= 30
  4856.0 2103.72  4868.3 2103.05  4873.8 2101.75  4879.1 2102.11  4889.3 2099.14
  4905.9 2092.65  4911.1 2094.30  4920.8 2092.42  4931.3 2091.96  4937.9 2090.94
  4943.2 2094.20  4952.3 2089.33  4971.5 2083.56  4991.2 2082.05  4991.5 2081.55
  4995.0 2081.55  4995.2 2082.05  5004.8 2083.49  5015.3 2086.45  5022.0 2087.33
  5027.2 2090.26  5036.3 2089.01  5046.8 2088.99  5059.6 2093.82  5067.8 2095.90
  5091.9 2096.57  5110.0 2096.36  5119.0 2096.14  5130.7 2097.92  5147.6 2097.75
#Mann=5,-1,0
  4856.0    0.07       0  4971.5    0.16       0  4991.2    0.07       0
  4995.2    0.16       0  5110.0    0.07       0
Bank Sta=4991.2,4995.2
Exp/Cntr=0.3,0.1

Type RM Length L Ch R = 1,1042,80,80,80
BEGIN DESCRIPTION:
Elm 61 1042.23
END DESCRIPTION:
XS GIS Cut Line= 3
      1521940.43      6769444.08      1522055.49      6769492.93
      1522207.38      6769415.90
#Sta/Elev= 30
  4876.1 2100.73  4881.3 2100.73  4898.1 2098.75  4903.6 2093.31  4913.7 2095.13
  4921.8 2095.05  4925.8 2093.02  4927.2 2092.31  4935.4 2091.33  4945.5 2087.02
  4950.9 2086.19  4957.1 2083.85  4974.6 2081.40  4996.1 2080.13  4996.4 2079.63
  4999.9 2079.63  5000.1 2080.13  5020.2 2080.56  5056.6 2084.84  5064.7 2085.31
  5070.3 2088.35  5079.0 2089.75  5087.0 2091.72  5092.6 2094.09  5101.5 2093.67
  5114.9 2094.82  5132.5 2094.96  5153.8 2095.79  5159.4 2096.79  5171.4 2096.61
#Mann=5,-1,0
  4876.1    0.07       0  4925.8    0.16       0  4996.1    0.07       0
  5000.1    0.16       0  5132.5    0.07       0
Bank Sta=4996.1,5000.1
Exp/Cntr=0.3,0.1

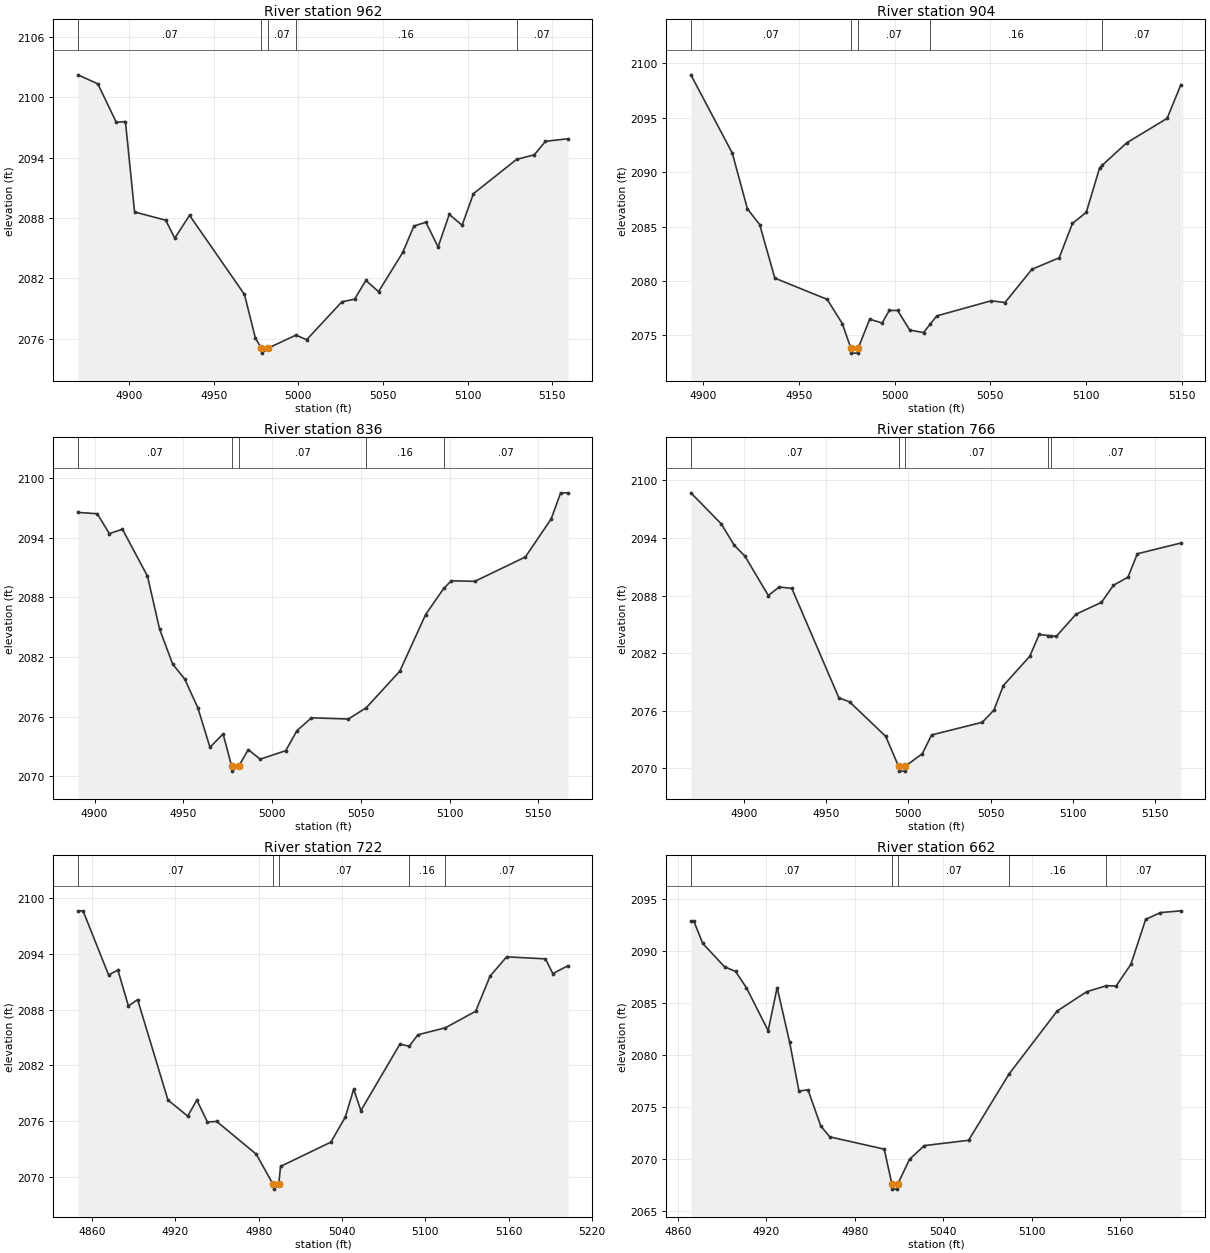
Type RM Length L Ch R = 1,962,58,58,58
BEGIN DESCRIPTION:
Elm 61 962.42
END DESCRIPTION:
XS GIS Cut Line= 3
      1522039.22      6769658.93      1522090.21      6769536.33
      1522208.04      6769432.55
#Sta/Elev= 30
  4869.6 2102.25  4881.4 2101.35  4892.3 2097.52  4897.7 2097.60  4903.1 2088.60
  4921.5 2087.78  4926.9 2085.99  4935.6 2088.27  4968.1 2080.39  4974.6 2076.02
  4978.1 2075.05  4978.3 2074.55  4982.1 2075.05  4998.5 2076.34  5004.9 2075.89
  5025.7 2079.66  5033.2 2079.92  5039.9 2081.78  5047.4 2080.67  5061.7 2084.57
  5068.3 2087.20  5075.4 2087.58  5082.6 2085.12  5089.2 2088.36  5096.8 2087.28
  5103.5 2090.42  5129.0 2093.83  5139.5 2094.29  5146.1 2095.63  5159.4 2095.89
#Mann=5,-1,0
  4869.6    0.07       0  4978.1    0.07       0  4982.1    0.07       0
  4998.5    0.16       0  5129.0    0.07       0
Bank Sta=4978.1,4982.1
Exp/Cntr=0.3,0.1

Type RM Length L Ch R = 1,904,68,68,68
BEGIN DESCRIPTION:
Elm 61 903.92
END DESCRIPTION:
XS GIS Cut Line= 3
      1522068.52      6769652.42      1522134.70      6769572.14
      1522239.80      6769462.79
#Sta/Elev= 30
  4893.7 2098.94  4915.3 2091.75  4923.2 2086.63  4929.6 2085.18  4937.5 2080.26
  4964.8 2078.31  4972.7 2076.09  4977.1 2073.87  4977.4 2073.37  4980.9 2073.37
  4981.1 2073.87  4987.0 2076.49  4993.5 2076.14  4997.2 2077.29  5001.6 2077.29
  5007.9 2075.49  5015.1 2075.26  5018.6 2076.04  5022.0 2076.79  5050.4 2078.18
  5057.6 2078.02  5071.7 2081.08  5085.9 2082.13  5092.8 2085.29  5100.0 2086.30
  5107.0 2090.40  5108.4 2090.64  5121.1 2092.69  5142.2 2094.94  5149.4 2098.04
#Mann=5,-1,0
  4893.7    0.07       0  4977.1    0.07       0  4981.1    0.07       0
  5018.6    0.16       0  5108.4    0.07       0
Bank Sta=4977.1,4981.1
Exp/Cntr=0.3,0.1

Type RM Length L Ch R = 1,836,70,70,70
BEGIN DESCRIPTION:
Elm 61 835.63
END DESCRIPTION:
XS GIS Cut Line= 3
      1522110.85      6769699.06      1522184.61      6769618.79
      1522286.59      6769486.44
#Sta/Elev= 30
  4890.6 2096.55  4901.5 2096.42  4908.3 2094.42  4915.7 2094.86  4929.8 2090.14
  4936.6 2084.83  4944.0 2081.30  4950.8 2079.79  4958.2 2076.89  4965.0 2072.94
  4972.4 2074.28  4977.2 2071.04  4977.4 2070.54  4981.2 2071.04  4986.6 2072.70
  4993.3 2071.74  5007.7 2072.60  5014.0 2074.61  5022.2 2075.90  5043.0 2075.78
  5053.1 2076.92  5072.0 2080.60  5086.5 2086.28  5096.7 2088.91  5101.0 2089.68
  5114.2 2089.62  5142.7 2092.07  5157.2 2095.88  5162.6 2098.52  5166.7 2098.52
#Mann=5,-1,0
  4890.6    0.07       0  4977.2    0.07       0  4981.2    0.07       0
  5053.1    0.16       0  5096.7    0.07       0
Bank Sta=4977.2,4981.2
Exp/Cntr=0.3,0.1

Type RM Length L Ch R = 1,766,44,44,44
BEGIN DESCRIPTION:
Elm 61 766.03
END DESCRIPTION:
XS GIS Cut Line= 3
      1522134.85      6769754.18      1522232.47      6769670.88
      1522313.98      6769522.08
#Sta/Elev= 30
  4867.7 2098.70  4886.3 2095.44  4894.0 2093.25  4900.5 2092.12  4914.8 2088.00
  4921.4 2088.89  4929.1 2088.74  4957.7 2077.34  4964.2 2076.92  4986.2 2073.32
  4994.0 2070.20  4994.3 2069.70  4997.8 2069.70  4998.0 2070.20  5008.4 2071.51
  5014.1 2073.47  5044.9 2074.79  5052.0 2076.06  5057.7 2078.61  5073.8 2081.67
  5079.5 2083.94  5085.0 2083.83  5087.0 2083.79  5089.9 2083.74  5101.9 2086.05
  5117.4 2087.29  5124.7 2089.07  5133.5 2089.91  5139.2 2092.35  5165.7 2093.47
#Mann=5,-1,0
  4867.7    0.07       0  4994.0    0.07       0  4998.0    0.07       0
  5085.0    0.16       0  5087.0    0.07       0
Bank Sta=4994,4998
Exp/Cntr=0.3,0.1

Type RM Length L Ch R = 1,722,60,60,60
BEGIN DESCRIPTION:
Elm 61 721.52
END DESCRIPTION:
XS GIS Cut Line= 3
      1522154.37      6769798.45      1522265.02      6769702.13
      1522323.61      6769504.22
#Sta/Elev= 30
  4849.7 2098.65  4853.4 2098.65  4871.8 2091.74  4878.5 2092.26  4886.1 2088.39
  4892.7 2089.08  4914.6 2078.24  4928.8 2076.52  4935.4 2078.24  4943.0 2075.88
  4949.7 2075.94  4978.2 2072.41  4990.4 2069.14  4990.7 2068.64  4994.4 2069.14
  4995.7 2071.09  5032.0 2073.71  5042.4 2076.42  5048.4 2079.42  5053.6 2077.11
  5081.7 2084.27  5088.5 2084.05  5094.6 2085.28  5114.5 2086.04  5136.3 2087.82
  5146.7 2091.61  5158.6 2093.69  5186.6 2093.47  5191.9 2091.88  5202.8 2092.73
#Mann=5,-1,0
  4849.7    0.07       0  4990.4    0.07       0  4994.4    0.07       0
  5088.5    0.16       0  5114.5    0.07       0
Bank Sta=4990.4,4994.4
Exp/Cntr=0.3,0.1

Type RM Length L Ch R = 1,662,87,87,87
BEGIN DESCRIPTION:
Elm 61 662.08
END DESCRIPTION:
XS GIS Cut Line= 3
      1522237.66      6769842.77      1522311.89      6769737.28
      1522319.71      6769534.12
#Sta/Elev= 30
  4868.9 2092.87  4870.9 2092.87  4876.9 2090.74  4891.7 2088.49  4899.2 2088.04
  4906.5 2086.49  4921.3 2082.35  4927.4 2086.49  4935.9 2081.22  4942.2 2076.55
  4948.3 2076.67  4957.0 2073.19  4963.1 2072.15  5000.0 2070.97  5005.2 2067.63
  5005.4 2067.13  5008.9 2067.13  5009.2 2067.63  5017.2 2070.00  5027.2 2071.31
  5057.2 2071.82  5084.7 2078.20  5117.3 2084.24  5137.3 2086.09  5150.7 2086.67
  5157.3 2086.64  5167.3 2088.73  5177.3 2093.04  5187.3 2093.69  5201.2 2093.86
#Mann=5,-1,0
  4868.9    0.07       0  5005.2    0.07       0  5009.2    0.07       0
  5084.7    0.16       0  5150.7    0.07       0
Bank Sta=5005.2,5009.2
Exp/Cntr=0.3,0.1

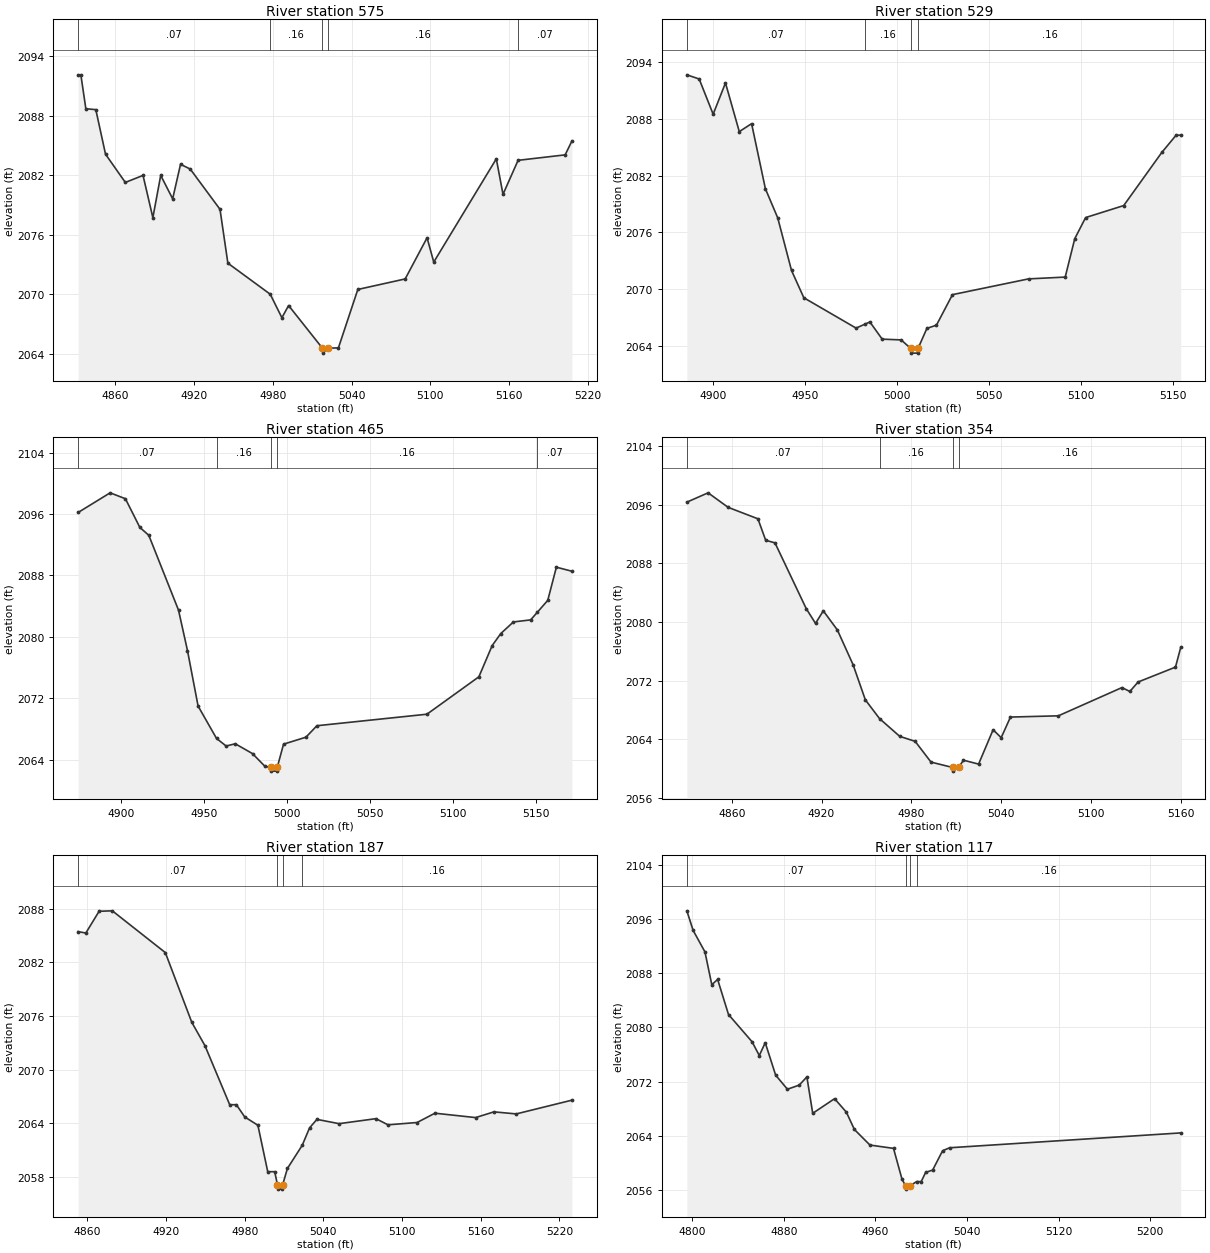
Type RM Length L Ch R = 1,575,46,46,46
BEGIN DESCRIPTION:
Elm 61 575.46
END DESCRIPTION:
XS GIS Cut Line= 3
      1522516.28      6769845.33      1522404.34      6769771.14
      1522360.08      6769532.91
#Sta/Elev= 30
  4831.5 2092.11  4833.6 2092.11  4837.4 2088.69  4845.0 2088.60  4852.4 2084.11
  4867.5 2081.26  4881.0 2081.97  4888.5 2077.71  4894.5 2081.97  4903.6 2079.61
  4909.6 2083.09  4917.0 2082.61  4939.7 2078.55  4945.7 2073.12  4978.0 2069.99
  4986.9 2067.62  4992.0 2068.85  5017.8 2064.55  5018.1 2064.05  5021.8 2064.55
  5030.0 2064.58  5044.8 2070.47  5080.9 2071.53  5097.6 2075.68  5102.7 2073.23
  5150.4 2083.64  5155.5 2080.06  5167.0 2083.49  5202.9 2084.04  5208.1 2085.45
#Mann=5,-1,0
  4831.5    0.07       0  4978.0    0.16       0  5017.8    0.07       0
  5021.8    0.16       0  5167.0    0.07       0
Bank Sta=5017.8,5021.8
Exp/Cntr=0.3,0.1

Type RM Length L Ch R = 1,529,64,64,64
BEGIN DESCRIPTION:
Elm 61 528.977
END DESCRIPTION:
XS GIS Cut Line= 3
      1522530.04      6769813.03      1522444.58      6769736.98
      1522405.01      6769588.04
#Sta/Elev= 30
  4885.6 2092.66  4892.3 2092.22  4899.9 2088.49  4906.6 2091.80  4914.1 2086.65
  4920.8 2087.49  4928.3 2080.60  4935.0 2077.52  4942.5 2071.95  4949.2 2069.06
  4977.6 2065.85  4982.7 2066.29  4985.1 2066.50  4991.8 2064.68  5002.1 2064.60
  5007.3 2063.70  5007.5 2063.20  5011.0 2063.20  5011.3 2063.70  5016.1 2065.82
  5021.3 2066.16  5030.0 2069.39  5071.4 2071.06  5091.3 2071.25  5096.5 2075.32
  5102.4 2077.55  5123.1 2078.82  5143.8 2084.44  5151.6 2086.27  5154.1 2086.27
#Mann=4,-1,0
  4885.6    0.07       0  4982.7    0.16       0  5007.3    0.07       0
  5011.3    0.16       0
Bank Sta=5007.3,5011.3
Exp/Cntr=0.3,0.1

Type RM Length L Ch R = 1,465,111,111,111
BEGIN DESCRIPTION:
Elm 61 4923
END DESCRIPTION:
XS GIS Cut Line= 3
      1522546.27      6769814.12      1522495.35      6769698.76
      1522447.30      6769534.13
#Sta/Elev= 30
  4873.9 2096.20  4893.2 2098.76  4902.4 2097.99  4911.1 2094.26  4916.5 2093.23
  4934.4 2083.49  4939.8 2078.23  4946.2 2071.00  4957.3 2066.79  4963.1 2065.80
  4968.6 2066.09  4979.0 2064.81  4986.5 2063.15  4989.9 2063.03  4990.2 2062.53
  4993.7 2062.53  4993.9 2063.03  4997.7 2066.04  5011.2 2066.95  5017.8 2068.44
  5084.1 2069.94  5115.4 2074.81  5123.4 2078.87  5128.6 2080.44  5136.2 2081.95
  5146.6 2082.22  5150.7 2083.23  5156.9 2084.76  5162.1 2089.08  5171.5 2088.55
#Mann=5,-1,0
  4873.9    0.07       0  4957.3    0.16       0  4989.9    0.07       0
  4993.9    0.16       0  5150.7    0.07       0
Bank Sta=4989.9,4993.9
Exp/Cntr=0.3,0.1

Type RM Length L Ch R = 1,354,167,167,167
BEGIN DESCRIPTION:
Elm 61 4922
END DESCRIPTION:
XS GIS Cut Line= 3
      1522555.37      6769854.52      1522603.50      6769691.47
      1522548.25      6769541.21
#Sta/Elev= 30
  4830.0 2096.35  4844.2 2097.62  4857.6 2095.64  4877.5 2094.08  4882.7 2091.15
  4888.9 2090.80  4909.8 2081.83  4916.0 2079.82  4921.2 2081.53  4930.6 2078.93
  4941.1 2074.19  4949.3 2069.40  4958.8 2066.84  4972.3 2064.42  4982.6 2063.74
  4993.2 2060.91  5007.6 2060.18  5007.8 2059.68  5011.6 2060.18  5014.9 2061.17
  5025.0 2060.64  5034.7 2065.32  5040.1 2064.24  5046.3 2067.05  5078.3 2067.22
  5120.8 2071.07  5126.1 2070.54  5131.6 2071.83  5156.6 2073.86  5160.1 2076.54
#Mann=4,-1,0
  4830.0    0.07       0  4958.8    0.16       0  5007.6    0.07       0
  5011.6    0.16       0
Bank Sta=5007.6,5011.6
Exp/Cntr=0.3,0.1

Type RM Length L Ch R = 1,187,70,70,70
BEGIN DESCRIPTION:
Elm 61 4921
END DESCRIPTION:
XS GIS Cut Line= 3
      1522714.24      6769933.89      1522733.64      6769788.18
      1522632.67      6769581.98
#Sta/Elev= 30
  4853.0 2085.43  4858.9 2085.28  4869.0 2087.71  4879.1 2087.76  4919.5 2083.09
  4939.7 2075.29  4949.7 2072.69  4968.6 2066.08  4973.7 2066.08  4980.0 2064.72
  4990.1 2063.78  4997.6 2058.59  5002.9 2058.59  5005.0 2057.14  5005.3 2056.64
  5008.8 2056.64  5009.0 2057.14  5012.6 2058.95  5023.9 2061.54  5029.5 2063.49
  5035.1 2064.44  5052.0 2063.96  5080.1 2064.52  5089.3 2063.83  5111.5 2064.09
  5125.1 2065.13  5156.1 2064.64  5170.1 2065.28  5187.1 2065.05  5229.6 2066.59
#Mann=4,-1,0
  4853.0    0.07       0  5005.0    0.07       0  5009.0    0.07       0
  5023.9    0.16       0
Bank Sta=5005,5009
Exp/Cntr=0.3,0.1

Type RM Length L Ch R = 1,117,0,0,0
BEGIN DESCRIPTION:
Elm 61 4920
END DESCRIPTION:
XS GIS Cut Line= 3
      1522754.60      6769983.37      1522803.47      6769784.48
      1522672.57      6769599.27
#Sta/Elev= 30
  4795.2 2097.19  4800.7 2094.30  4811.0 2091.14  4817.0 2086.30  4822.1 2087.07
  4831.6 2081.90  4852.2 2077.88  4858.5 2075.85  4863.7 2077.74  4872.8 2072.96
  4883.1 2070.88  4893.4 2071.49  4900.1 2072.70  4905.2 2067.33  4924.3 2069.49
  4934.6 2067.50  4941.6 2064.95  4955.2 2062.65  4975.8 2062.16  4983.2 2057.63
  4986.3 2056.65  4986.6 2056.15  4990.3 2056.65  4996.0 2057.26  5000.0 2057.26
  5003.9 2058.62  5010.0 2058.96  5018.7 2061.81  5024.8 2062.25  5226.8 2064.44
#Mann=4,-1,0
  4795.2    0.07       0  4986.3    0.07       0  4990.3    0.07       0
  4996.0    0.16       0
Bank Sta=4986.3,4990.3
Exp/Cntr=0.3,0.1

Chan Stop Cuts=-1