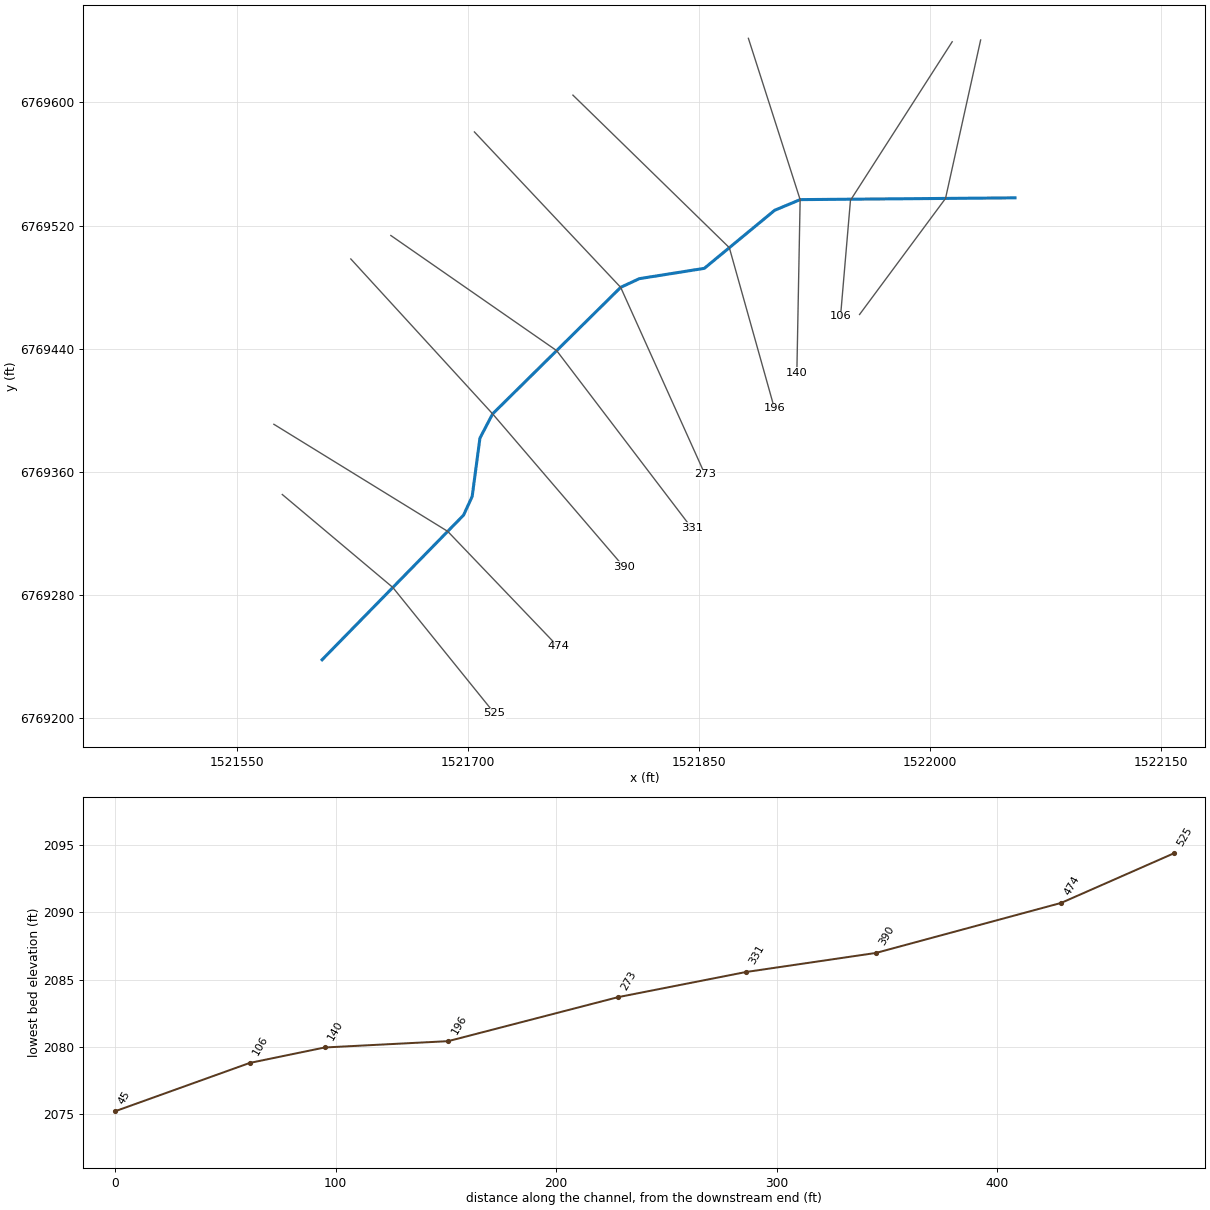
--- Elm 62.prj (project) ---

Proj Title=Elm 62 Base Level Engineering
Current Plan=p01
Default Exp/Contr=0.3,0.1
English Units
Geom File=g01
Flow File=f01
Plan File=p01
BEGIN DESCRIPTION:
Elm 62
END DESCRIPTION:

--- Elm 62.p01 (plan) ---

Plan Title=Multiple Run
Short Identifier=Multiple
Geom File=g01
Flow File=f01
Subcritical Flow
K Sum by GR= 0
Std Step Tol= 0.01
Critical Tol= 0.01
Num of Std Step Trials= 20
Max Error Tol= 0.3
Flow Tol Ratio= 0.001
Split Flow NTrial= 30
Split Flow Tol= 0.02
Split Flow Ratio= 0.02
Log Output Level= 0
Friction Slope Method= 1
Unsteady Friction Slope Method= 2
Unsteady Bridges Friction Slope Method= 1
Parabolic Critical Depth
Global Vel Dist=  1 , 1 , 1
Global Log Level= 0
CheckData=True
Encroach Param= -1, 0, 0, 0
BEGIN DESCRIPTION:
Multiple Run
END DESCRIPTION:

--- Elm 62.f01 (steady flow) ---

Flow Title=Multiple
Number of Profiles=7
Profile Names=10-year,25-year,50-year,1pct_min,100-year,1pct_plu,500-year
River Rch & RM= Elm 62,Reach-1,525
      30      36      40      29      46      63      59
River Rch & RM= Elm 62,Reach-1,45
      62      80      94      69     110     152     154
Boundary for River Rch & Prof#=Elm 62,Reach-1,1
Up Type=0
Dn Type=3
Dn Slope=0.005
Boundary for River Rch & Prof#=Elm 62,Reach-1,2
Up Type=0
Dn Type=3
Dn Slope=0.005
Boundary for River Rch & Prof#=Elm 62,Reach-1,3
Up Type=0
Dn Type=3
Dn Slope=0.005
Boundary for River Rch & Prof#=Elm 62,Reach-1,4
Up Type=0
Dn Type=3
Dn Slope=0.005
Boundary for River Rch & Prof#=Elm 62,Reach-1,5
Up Type=0
Dn Type=3
Dn Slope=0.005
Boundary for River Rch & Prof#=Elm 62,Reach-1,6
Up Type=0
Dn Type=3
Dn Slope=0.005
Boundary for River Rch & Prof#=Elm 62,Reach-1,7
Up Type=0
Dn Type=3
Dn Slope=0.005

--- Elm 62.g01 (geometry) ---

Geom Title=Existing Conditions

River Reach=Elm 62,Reach-1
Reach XY= 14
      1521605.00      6769238.00      1521650.95      6769284.97
      1521696.89      6769331.93      1521702.48      6769344.05
      1521707.52      6769381.97      1521715.76      6769397.70
      1521757.35      6769438.78      1521798.93      6769479.87
      1521811.02      6769485.51      1521853.25      6769492.22
      1521898.92      6769529.92      1521915.48      6769536.85
      1521985.24      6769537.43      1522055.00      6769538.00

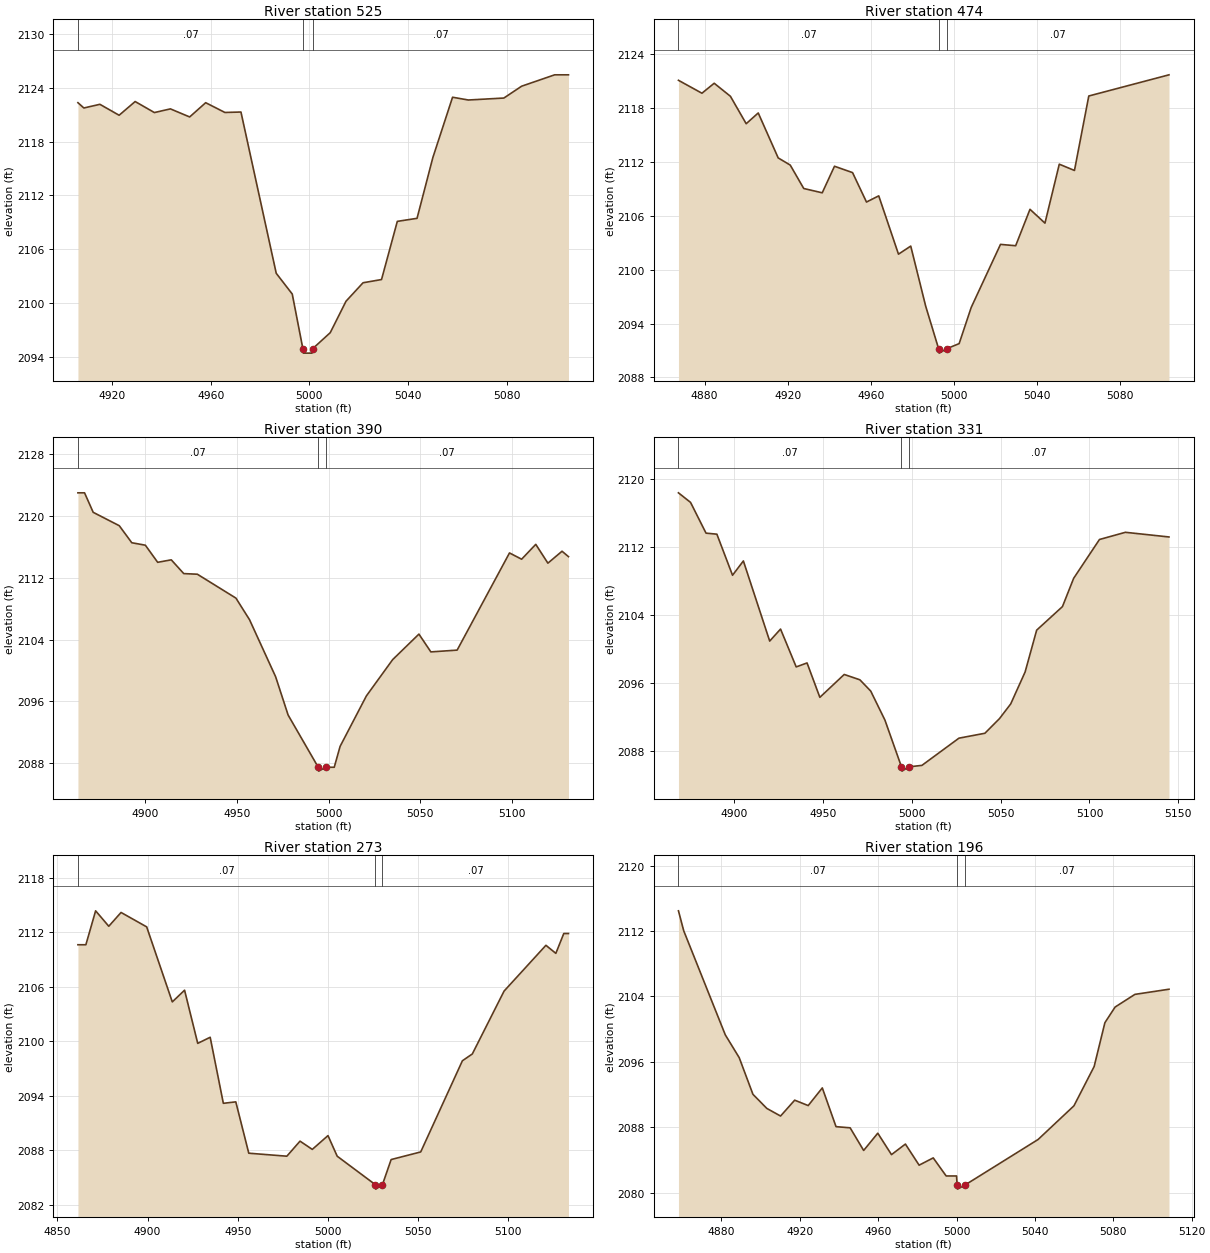
Type RM Length L Ch R = 1,525,51,51,51
BEGIN DESCRIPTION:
Elm 62 5014
END DESCRIPTION:
XS GIS Cut Line= 3
      1521579.16      6769345.34      1521650.95      6769284.97
      1521716.97      6769203.19
#Sta/Elev= 30
  4906.2 2122.33  4908.6 2121.74  4915.1 2122.15  4922.9 2120.93  4929.4 2122.46
  4937.2 2121.23  4943.7 2121.64  4951.5 2120.74  4958.0 2122.33  4965.8 2121.24
  4972.3 2121.29  4986.6 2103.30  4993.1 2100.98  4997.4 2094.89  4997.6 2094.39
  5001.1 2094.39  5001.4 2094.89  5008.5 2096.67  5014.9 2100.18  5021.8 2102.24
  5029.3 2102.60  5035.7 2109.09  5043.7 2109.43  5050.1 2116.20  5058.1 2122.94
  5064.5 2122.63  5078.9 2122.85  5086.1 2124.17  5099.5 2125.44  5105.1 2125.44
#Mann=3,-1,0
  4906.2    0.07       0  4997.4    0.07       0  5001.4    0.07       0
Bank Sta=4997.4,5001.4
Exp/Cntr=0.3,0.1

Type RM Length L Ch R = 1,474,84,84,84
BEGIN DESCRIPTION:
Elm 62 5013
END DESCRIPTION:
XS GIS Cut Line= 3
      1521573.69      6769390.95      1521686.59      6769321.40
      1521758.16      6769246.64
#Sta/Elev= 30
  4867.4 2121.12  4878.7 2119.68  4884.6 2120.79  4892.4 2119.34  4900.0 2116.28
  4905.8 2117.48  4915.4 2112.47  4921.2 2111.67  4927.7 2109.06  4936.6 2108.58
  4942.5 2111.54  4951.2 2110.83  4957.9 2107.55  4963.8 2108.24  4973.3 2101.74
  4979.2 2102.64  4986.4 2095.94  4992.6 2091.21  4992.9 2090.71  4996.6 2091.21
  5002.5 2091.77  5008.3 2095.80  5022.4 2102.83  5029.7 2102.68  5036.6 2106.74
  5043.8 2105.20  5050.7 2111.77  5058.0 2111.07  5064.9 2119.37  5103.5 2121.73
#Mann=3,-1,0
  4867.4    0.07       0  4992.6    0.07       0  4996.6    0.07       0
Bank Sta=4992.6,4996.6
Exp/Cntr=0.3,0.1

Type RM Length L Ch R = 1,390,59,59,59
BEGIN DESCRIPTION:
Elm 62 5012
END DESCRIPTION:
XS GIS Cut Line= 3
      1521623.67      6769498.31      1521715.76      6769397.70
      1521800.78      6769298.56
#Sta/Elev= 30
  4863.6 2122.96  4867.2 2122.96  4871.9 2120.44  4886.1 2118.71  4892.9 2116.51
  4900.3 2116.19  4907.0 2113.98  4914.4 2114.30  4921.2 2112.52  4928.6 2112.44
  4949.6 2109.35  4957.0 2106.56  4971.2 2099.19  4978.0 2094.24  4994.4 2087.49
  4994.7 2086.99  4998.4 2087.49  5003.1 2087.49  5006.3 2090.19  5020.6 2096.71
  5034.9 2101.40  5049.2 2104.70  5055.7 2102.40  5070.0 2102.63  5098.5 2115.19
  5105.1 2114.38  5112.8 2116.30  5119.4 2113.87  5127.1 2115.41  5130.6 2114.71
#Mann=3,-1,0
  4863.6    0.07       0  4994.4    0.07       0  4998.4    0.07       0
Bank Sta=4994.4,4998.4
Exp/Cntr=0.3,0.1

Type RM Length L Ch R = 1,331,58,58,58
BEGIN DESCRIPTION:
Elm 62 5011
END DESCRIPTION:
XS GIS Cut Line= 3
      1521649.66      6769513.55      1521757.35      6769438.78
      1521844.99      6769323.65
#Sta/Elev= 30
  4868.9 2118.42  4875.7 2117.29  4884.4 2113.66  4890.5 2113.54  4899.3 2108.69
  4905.4 2110.38  4920.2 2100.92  4926.3 2102.34  4935.1 2097.87  4941.2 2098.34
  4948.4 2094.28  4962.1 2096.98  4970.9 2096.35  4977.0 2095.02  4985.0 2091.59
  4994.3 2086.07  4994.6 2085.57  4998.3 2086.07  5005.8 2086.25  5026.6 2089.46
  5041.2 2090.04  5049.4 2091.77  5055.7 2093.50  5063.8 2097.27  5070.3 2102.21
  5084.8 2104.99  5091.1 2108.33  5105.6 2112.91  5120.2 2113.76  5144.7 2113.21
#Mann=3,-1,0
  4868.9    0.07       0  4994.3    0.07       0  4998.3    0.07       0
Bank Sta=4994.3,4998.3
Exp/Cntr=0.3,0.1

Type RM Length L Ch R = 1,273,77,77,77
BEGIN DESCRIPTION:
Elm 62 5010
END DESCRIPTION:
XS GIS Cut Line= 3
      1521703.94      6769580.80      1521798.93      6769479.87
      1521853.69      6769358.34
#Sta/Elev= 30
  4861.4 2110.64  4865.8 2110.64  4871.2 2114.38  4878.5 2112.68  4885.3 2114.20
  4899.5 2112.61  4913.7 2104.34  4920.5 2105.63  4927.8 2099.77  4934.7 2100.44
  4942.0 2093.16  4948.9 2093.32  4956.1 2087.66  4977.2 2087.33  4984.5 2088.99
  4991.3 2088.08  5000.0 2089.60  5005.1 2087.33  5026.2 2084.20  5026.5 2083.70
  5030.2 2084.20  5035.0 2086.96  5051.4 2087.80  5074.5 2097.85  5080.0 2098.60
  5097.6 2105.53  5120.8 2110.58  5126.3 2109.69  5130.7 2111.88  5133.3 2111.88
#Mann=3,-1,0
  4861.4    0.07       0  5026.2    0.07       0  5030.2    0.07       0
Bank Sta=5026.2,5030.2
Exp/Cntr=0.3,0.1

Type RM Length L Ch R = 1,196,56,56,56
BEGIN DESCRIPTION:
Elm 62 5008
END DESCRIPTION:
XS GIS Cut Line= 3
      1521767.92      6769604.71      1521869.50      6769505.63
      1521898.78      6769401.26
#Sta/Elev= 30
  4858.1 2114.47  4860.8 2112.02  4882.0 2099.30  4889.1 2096.51  4896.1 2092.03
  4903.2 2090.30  4910.2 2089.37  4917.4 2091.31  4924.3 2090.65  4931.5 2092.81
  4938.5 2088.07  4945.7 2087.93  4952.6 2085.16  4959.8 2087.27  4966.8 2084.65
  4973.9 2085.94  4980.9 2083.36  4988.1 2084.25  4994.7 2082.04  5000.0 2082.04
  5000.3 2080.93  5000.5 2080.43  5004.3 2080.93  5041.6 2086.50  5059.9 2090.62
  5070.2 2095.42  5075.7 2100.79  5080.9 2102.70  5091.0 2104.25  5108.4 2104.88
#Mann=3,-1,0
  4858.1    0.07       0  5000.3    0.07       0  5004.3    0.07       0
Bank Sta=5000.3,5004.3
Exp/Cntr=0.3,0.1

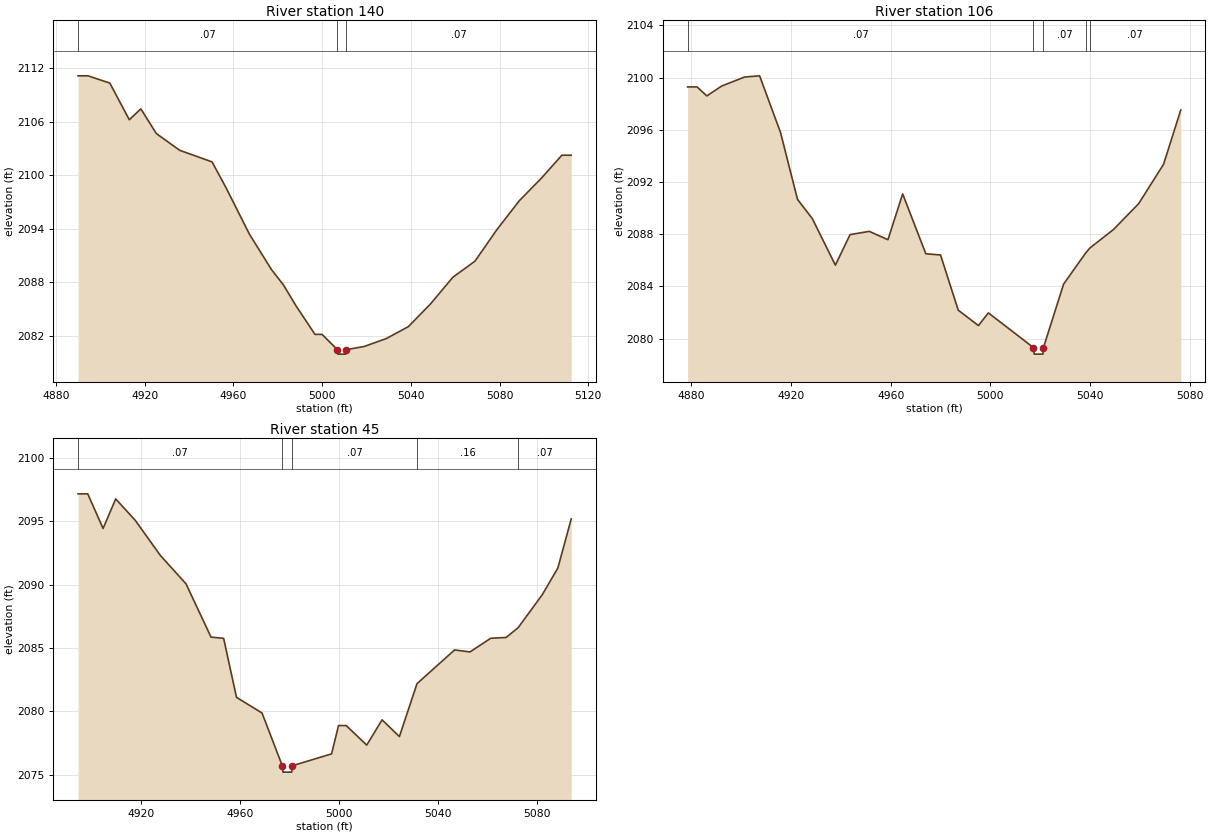
Type RM Length L Ch R = 1,140,34,34,34
BEGIN DESCRIPTION:
Elm 62 5007
END DESCRIPTION:
XS GIS Cut Line= 3
      1521881.88      6769641.60      1521915.48      6769536.85
      1521913.35      6769424.57
#Sta/Elev= 30
  4890.0 2111.13  4894.5 2111.13  4904.3 2110.32  4913.1 2106.21  4918.3 2107.43
  4925.3 2104.66  4935.8 2102.79  4950.4 2101.49  4956.8 2098.55  4967.3 2093.37
  4977.3 2089.39  4982.6 2087.70  4988.3 2085.35  4996.8 2082.17  5000.0 2082.17
  5006.9 2080.46  5007.1 2079.96  5010.6 2079.96  5010.9 2080.46  5018.9 2080.81
  5028.9 2081.70  5038.9 2083.04  5048.9 2085.59  5058.9 2088.56  5068.9 2090.37
  5078.9 2093.94  5088.9 2097.14  5098.9 2099.68  5108.1 2102.24  5112.3 2102.24
#Mann=3,-1,0
  4890.0    0.07       0  5006.9    0.07       0  5010.9    0.07       0
Bank Sta=5006.9,5010.9
Exp/Cntr=0.3,0.1

Type RM Length L Ch R = 1,106,61,61,61
BEGIN DESCRIPTION:
Elm 62 5006
END DESCRIPTION:
XS GIS Cut Line= 3
      1522014.24      6769639.38      1521948.16      6769536.40
      1521941.72      6769461.14
#Sta/Elev= 30
  4878.5 2099.29  4882.3 2099.29  4886.2 2098.60  4892.2 2099.36  4901.4 2100.05
  4907.4 2100.14  4915.8 2095.79  4922.6 2090.67  4928.5 2089.21  4937.8 2085.63
  4943.7 2087.97  4951.4 2088.22  4958.9 2087.58  4964.8 2091.09  4974.1 2086.50
  4980.0 2086.41  4987.1 2082.18  4995.2 2081.00  4999.2 2081.97  5017.3 2079.31
  5017.6 2078.81  5021.1 2078.81  5021.3 2079.31  5029.4 2084.18  5038.2 2086.55
  5039.9 2086.94  5049.4 2088.36  5059.5 2090.34  5069.5 2093.36  5076.4 2097.52
#Mann=5,-1,0
  4878.5    0.07       0  5017.3    0.07       0  5021.3    0.07       0
  5038.2    0.16       0  5039.9    0.07       0
Bank Sta=5017.3,5021.3
Exp/Cntr=0.3,0.1

Type RM Length L Ch R = 1,45,0,0,0
BEGIN DESCRIPTION:
Elm 62 5009
END DESCRIPTION:
XS GIS Cut Line= 3
      1522032.71      6769640.53      1522009.90      6769537.63
      1521954.08      6769462.25
#Sta/Elev= 30
  4894.6 2097.15  4898.5 2097.15  4904.7 2094.42  4909.8 2096.75  4917.7 2095.06
  4927.9 2092.28  4938.2 2090.06  4948.3 2085.86  4953.4 2085.76  4958.6 2081.11
  4968.9 2079.88  4977.1 2075.72  4977.4 2075.22  4980.9 2075.22  4981.1 2075.72
  4997.0 2076.66  4999.8 2078.89  5002.9 2078.89  5011.2 2077.35  5017.4 2079.34
  5024.4 2078.02  5031.5 2082.19  5046.7 2084.85  5052.9 2084.69  5061.3 2085.77
  5067.5 2085.83  5072.4 2086.61  5082.1 2089.20  5088.4 2091.30  5093.8 2095.17
#Mann=5,-1,0
  4894.6    0.07       0  4977.1    0.07       0  4981.1    0.07       0
  5031.5    0.16       0  5072.4    0.07       0
Bank Sta=4977.1,4981.1
Exp/Cntr=0.3,0.1

Chan Stop Cuts=-1