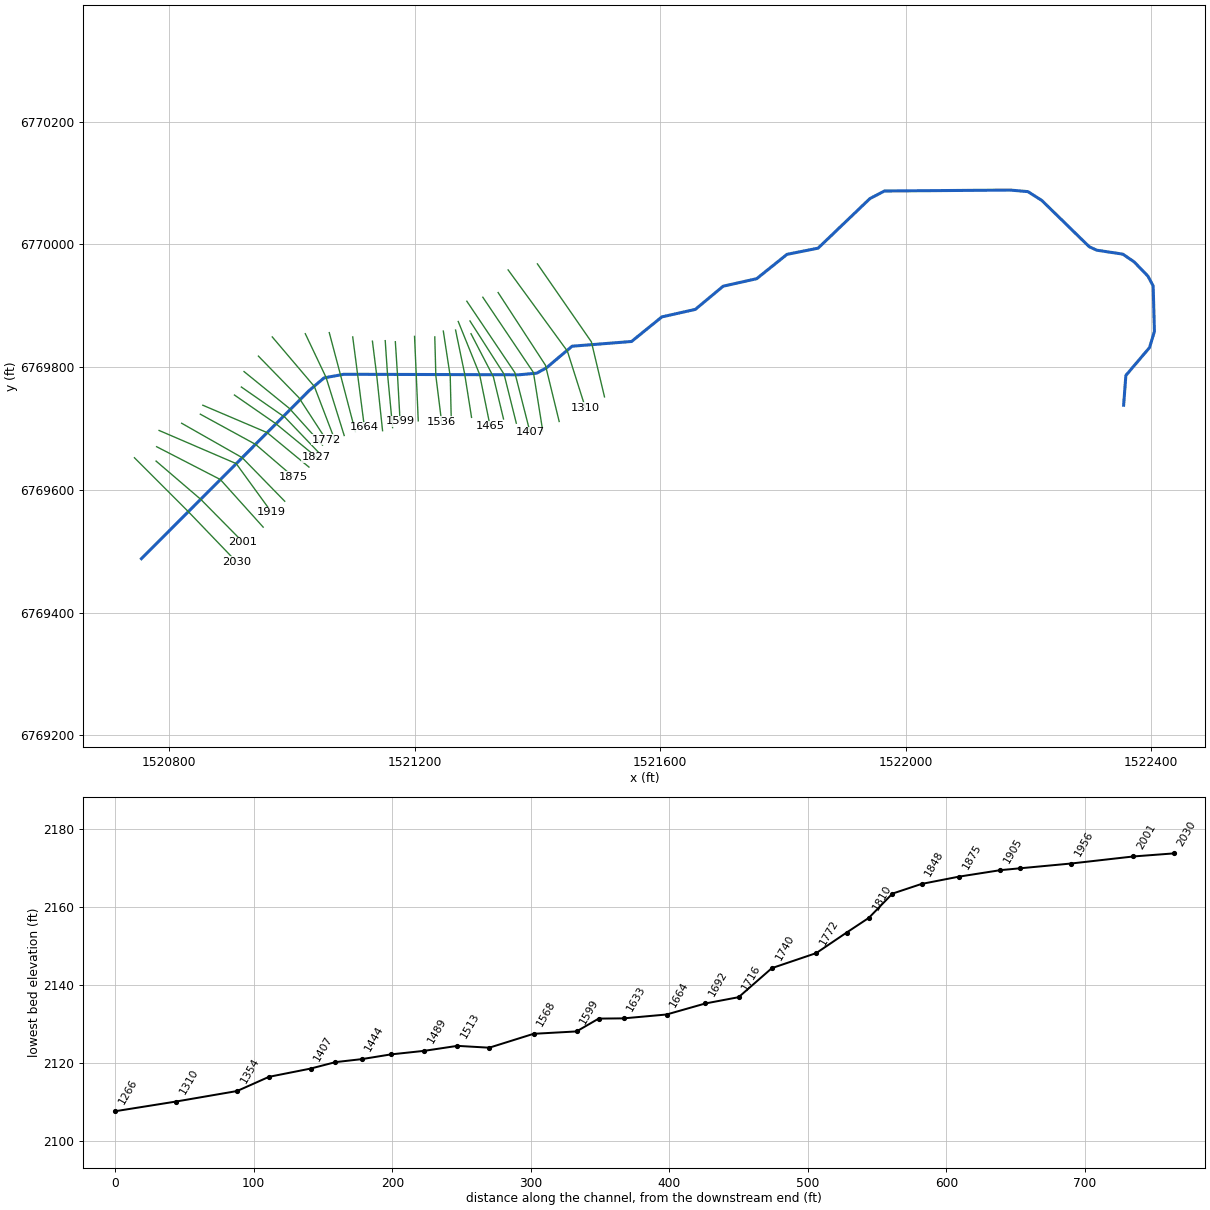
--- Elm 63.prj (project) ---

Proj Title=Elm 63 Base Level Engineering
Current Plan=p01
Default Exp/Contr=0.3,0.1
English Units
Geom File=g01
Flow File=f01
Plan File=p01
BEGIN DESCRIPTION:
Elm 63
END DESCRIPTION:

--- Elm 63.p01 (plan) ---

Plan Title=Multiple Run
Short Identifier=Multiple
Geom File=g01
Flow File=f01
Subcritical Flow
K Sum by GR= 0
Std Step Tol= 0.01
Critical Tol= 0.01
Num of Std Step Trials= 20
Max Error Tol= 0.3
Flow Tol Ratio= 0.001
Split Flow NTrial= 30
Split Flow Tol= 0.02
Split Flow Ratio= 0.02
Log Output Level= 0
Friction Slope Method= 1
Unsteady Friction Slope Method= 2
Unsteady Bridges Friction Slope Method= 1
Parabolic Critical Depth
Global Vel Dist=  1 , 1 , 1
Global Log Level= 0
CheckData=True
Encroach Param= -1, 0, 0, 0
BEGIN DESCRIPTION:
Multiple Run
END DESCRIPTION:

--- Elm 63.f01 (steady flow) ---

Flow Title=Multiple
Number of Profiles=7
Profile Names=10-year,25-year,50-year,1pct_min,100-year,1pct_plu,500-year
River Rch & RM= Elm 63,Reach-1,2030
      54      69      80      58      93     129     128
Boundary for River Rch & Prof#=Elm 63,Reach-1,1
Up Type=0
Dn Type=3
Dn Slope=0.005
Boundary for River Rch & Prof#=Elm 63,Reach-1,2
Up Type=0
Dn Type=3
Dn Slope=0.005
Boundary for River Rch & Prof#=Elm 63,Reach-1,3
Up Type=0
Dn Type=3
Dn Slope=0.005
Boundary for River Rch & Prof#=Elm 63,Reach-1,4
Up Type=0
Dn Type=3
Dn Slope=0.005
Boundary for River Rch & Prof#=Elm 63,Reach-1,5
Up Type=0
Dn Type=3
Dn Slope=0.005
Boundary for River Rch & Prof#=Elm 63,Reach-1,6
Up Type=0
Dn Type=3
Dn Slope=0.005
Boundary for River Rch & Prof#=Elm 63,Reach-1,7
Up Type=0
Dn Type=3
Dn Slope=0.005

--- Elm 63.g01 (geometry) ---

Geom Title=Existing Conditions

River Reach=Elm 63,Reach-1
Reach XY= 30
      1520755.00      6769488.00      1521028.13      6769761.83
      1521052.55      6769782.54      1521084.82      6769788.43
      1521370.18      6769787.57      1521399.06      6769790.26
      1521414.65      6769798.85      1521456.60      6769834.14
      1521553.42      6769841.83      1521602.82      6769881.88
      1521657.20      6769894.08      1521702.80      6769931.92
      1521757.20      6769944.08      1521806.74      6769983.81
      1521857.29      6769993.85      1521941.69      6770074.60
      1521965.44      6770086.95      1522170.20      6770088.49
      1522199.14      6770085.94      1522221.75      6770071.54
      1522298.98      6769996.19      1522311.09      6769990.56
      1522353.60      6769984.13      1522372.15      6769971.54
      1522394.70      6769948.11      1522403.12      6769932.29
      1522405.16      6769858.09      1522397.17      6769831.87
      1522358.65      6769786.49      1522355.00      6769738.00

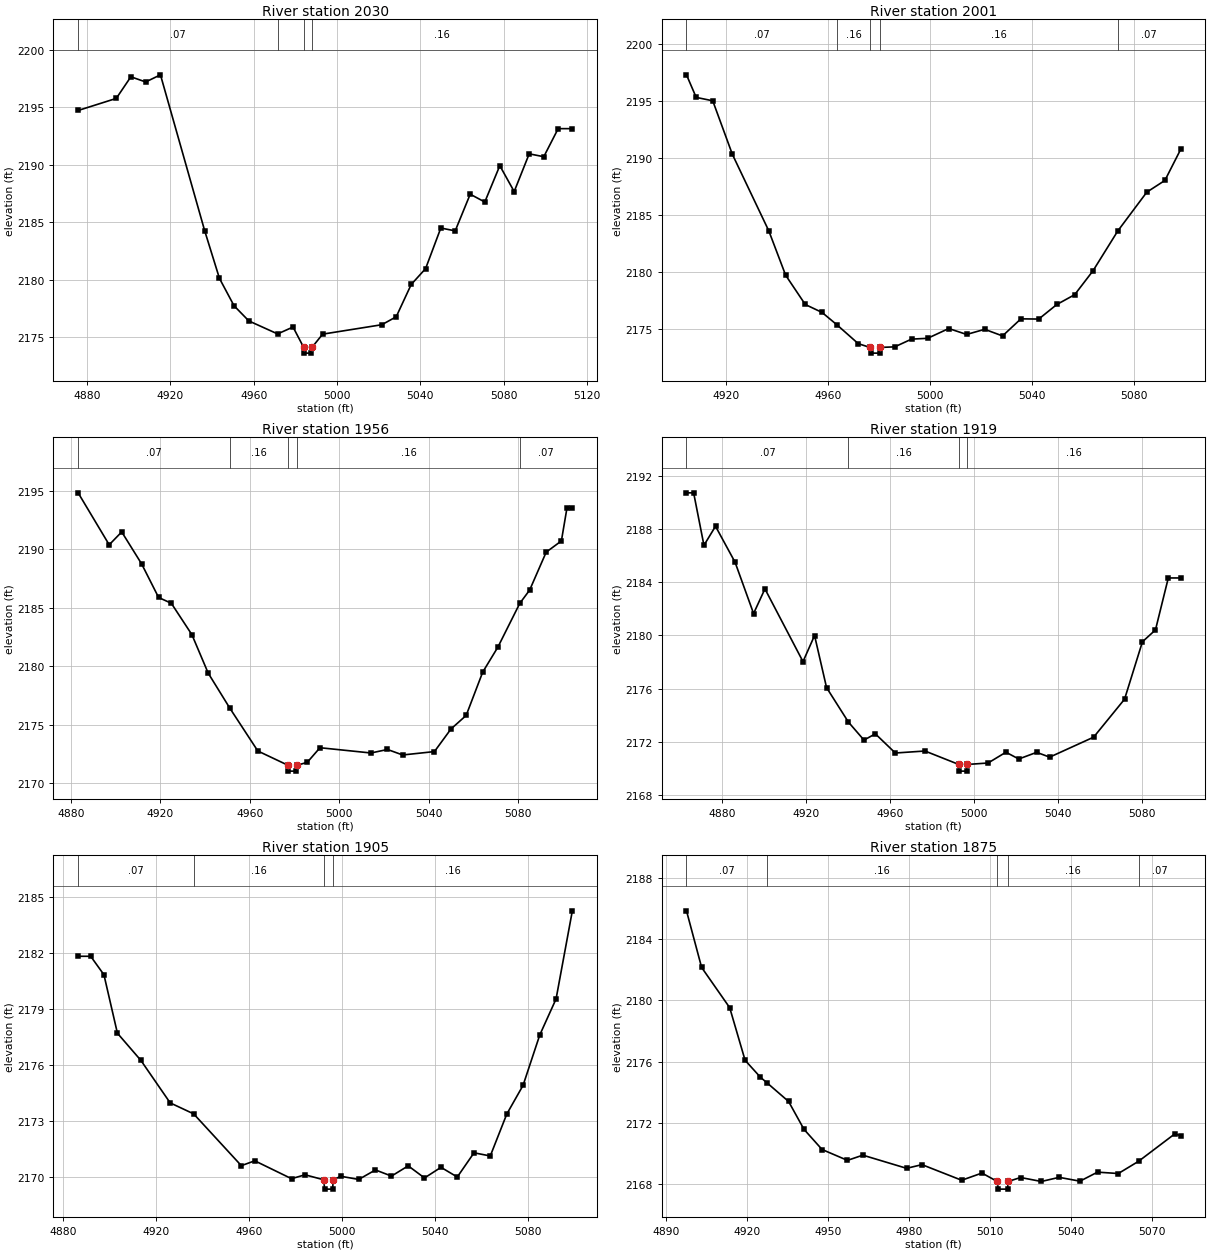
Type RM Length L Ch R = 1,2030,29,29,29
BEGIN DESCRIPTION:
Elm 63 4972
END DESCRIPTION:
XS GIS Cut Line= 3
      1520743.61      6769652.46      1520831.44      6769564.63
      1520909.63      6769483.19
#Sta/Elev= 30
  4875.8 2194.73  4894.1 2195.78  4901.1 2197.66  4908.2 2197.21  4915.3 2197.83
  4936.5 2184.28  4943.6 2180.13  4950.6 2177.75  4957.7 2176.43  4971.5 2175.30
  4978.9 2175.90  4984.0 2174.13  4984.2 2173.63  4987.7 2173.63  4988.0 2174.13
  4993.1 2175.28  5021.5 2176.10  5028.4 2176.79  5035.6 2179.60  5042.5 2180.98
  5049.8 2184.51  5056.7 2184.26  5063.9 2187.45  5070.9 2186.77  5078.1 2189.93
  5085.0 2187.68  5092.2 2190.96  5099.2 2190.71  5106.1 2193.15  5112.9 2193.15
#Mann=4,-1,0
  4875.8    0.07       0  4971.5    0.16       0  4984.0    0.07       0
  4988.0    0.16       0
Bank Sta=4984,4988
Exp/Cntr=0.3,0.1

Type RM Length L Ch R = 1,2001,45,45,45
BEGIN DESCRIPTION:
Elm 63 4996
END DESCRIPTION:
XS GIS Cut Line= 3
      1520778.93      6769646.98      1520851.54      6769584.79
      1520920.62      6769514.85
#Sta/Elev= 30
  4904.4 2197.28  4908.2 2195.30  4914.7 2195.00  4922.4 2190.30  4936.7 2183.58
  4943.3 2179.69  4951.0 2177.12  4957.6 2176.42  4963.5 2175.32  4971.8 2173.68
  4976.4 2173.35  4976.7 2172.85  4980.2 2172.85  4980.4 2173.35  4986.1 2173.40
  4992.7 2174.08  4999.0 2174.15  5007.3 2175.01  5014.3 2174.49  5021.4 2174.94
  5028.4 2174.36  5035.6 2175.86  5042.6 2175.84  5049.7 2177.12  5056.7 2177.98
  5063.9 2180.08  5073.6 2183.57  5085.0 2186.98  5092.1 2188.01  5098.3 2190.74
#Mann=5,-1,0
  4904.4    0.07       0  4963.5    0.16       0  4976.4    0.07       0
  4980.4    0.16       0  5073.6    0.07       0
Bank Sta=4976.4,4980.4
Exp/Cntr=0.3,0.1

Type RM Length L Ch R = 1,1956,37,37,37
BEGIN DESCRIPTION:
Elm 63 4995
END DESCRIPTION:
XS GIS Cut Line= 3
      1520779.78      6769670.44      1520883.61      6769616.95
      1520953.36      6769539.40
#Sta/Elev= 30
  4883.2 2194.82  4897.1 2190.38  4902.7 2191.48  4911.6 2188.75  4919.2 2185.88
  4924.9 2185.38  4934.1 2182.70  4941.4 2179.41  4951.1 2176.41  4963.6 2172.76
  4977.1 2171.54  4977.3 2171.04  4980.8 2171.04  4981.1 2171.54  4985.7 2171.79
  4991.4 2173.04  5014.2 2172.59  5021.6 2172.89  5028.4 2172.42  5042.6 2172.71
  5050.0 2174.64  5056.8 2175.80  5064.2 2179.50  5071.0 2181.64  5080.8 2185.38
  5085.2 2186.51  5092.6 2189.75  5099.4 2190.71  5101.9 2193.53  5104.3 2193.53
#Mann=5,-1,0
  4883.2    0.07       0  4951.1    0.16       0  4977.1    0.07       0
  4981.1    0.16       0  5080.8    0.07       0
Bank Sta=4977.1,4981.1
Exp/Cntr=0.3,0.1

Type RM Length L Ch R = 1,1919,14,14,14
BEGIN DESCRIPTION:
Elm 63 4971
END DESCRIPTION:
XS GIS Cut Line= 3
      1520783.79      6769696.92      1520909.46      6769642.86
      1520967.19      6769563.42
#Sta/Elev= 30
  4863.2 2190.70  4866.6 2190.70  4871.5 2186.76  4877.0 2188.19  4886.3 2185.49
  4895.1 2181.64  4900.5 2183.49  4918.6 2178.03  4924.1 2179.99  4929.8 2176.08
  4940.2 2173.49  4947.6 2172.14  4953.0 2172.61  4962.5 2171.17  4976.6 2171.32
  4992.7 2170.31  4992.9 2169.81  4996.4 2169.81  4996.7 2170.31  5006.6 2170.42
  5015.1 2171.23  5021.2 2170.72  5029.7 2171.22  5035.9 2170.86  5056.8 2172.36
  5071.5 2175.21  5080.0 2179.52  5086.2 2180.41  5092.3 2184.31  5098.2 2184.31
#Mann=4,-1,0
  4863.2    0.07       0  4940.2    0.16       0  4992.7    0.07       0
  4996.7    0.16       0
Bank Sta=4992.7,4996.7
Exp/Cntr=0.3,0.1

Type RM Length L Ch R = 1,1905,30,30,30
BEGIN DESCRIPTION:
Elm 63 4994
END DESCRIPTION:
XS GIS Cut Line= 3
      1520820.58      6769708.63      1520919.16      6769652.58
      1520988.45      6769581.60
#Sta/Elev= 30
  4886.6 2181.84  4892.0 2181.84  4897.7 2180.85  4903.5 2177.71  4913.6 2176.25
  4926.2 2173.97  4936.3 2173.38  4956.8 2170.60  4962.6 2170.86  4978.4 2169.90
  4984.2 2170.11  4992.3 2169.84  4992.6 2169.34  4996.1 2169.34  4996.3 2169.84
  4999.6 2170.03  5007.3 2169.86  5014.5 2170.37  5021.4 2170.04  5028.6 2170.59
  5035.6 2169.94  5042.7 2170.51  5049.7 2169.99  5056.9 2171.29  5063.9 2171.12
  5071.0 2173.37  5078.0 2174.91  5085.2 2177.62  5092.2 2179.55  5099.2 2184.28
#Mann=4,-1,0
  4886.6    0.07       0  4936.3    0.16       0  4992.3    0.07       0
  4996.3    0.16       0
Bank Sta=4992.3,4996.3
Exp/Cntr=0.3,0.1

Type RM Length L Ch R = 1,1875,27,27,27
BEGIN DESCRIPTION:
Elm 63 4993
END DESCRIPTION:
XS GIS Cut Line= 3
      1520850.96      6769723.39      1520940.83      6769674.31
      1521002.00      6769621.83
#Sta/Elev= 28
  4897.6 2185.86  4903.2 2182.16  4913.6 2179.53  4919.3 2176.09  4925.0 2174.98
  4927.4 2174.62  4935.4 2173.40  4941.1 2171.58  4947.8 2170.26  4957.2 2169.55
  4962.9 2169.89  4979.1 2169.03  4984.8 2169.27  4999.5 2168.25  5007.0 2168.72
  5012.7 2168.17  5013.0 2167.67  5016.5 2167.67  5016.7 2168.17  5021.3 2168.43
  5029.0 2168.17  5035.6 2168.44  5043.3 2168.19  5049.8 2168.78  5057.5 2168.69
  5065.0 2169.49  5078.4 2171.28  5080.6 2171.16
#Mann=5,-1,0
  4897.6    0.07       0  4927.4    0.16       0  5012.7    0.07       0
  5016.7    0.16       0  5065.0    0.07       0
Bank Sta=5012.7,5016.7
Exp/Cntr=0.3,0.1

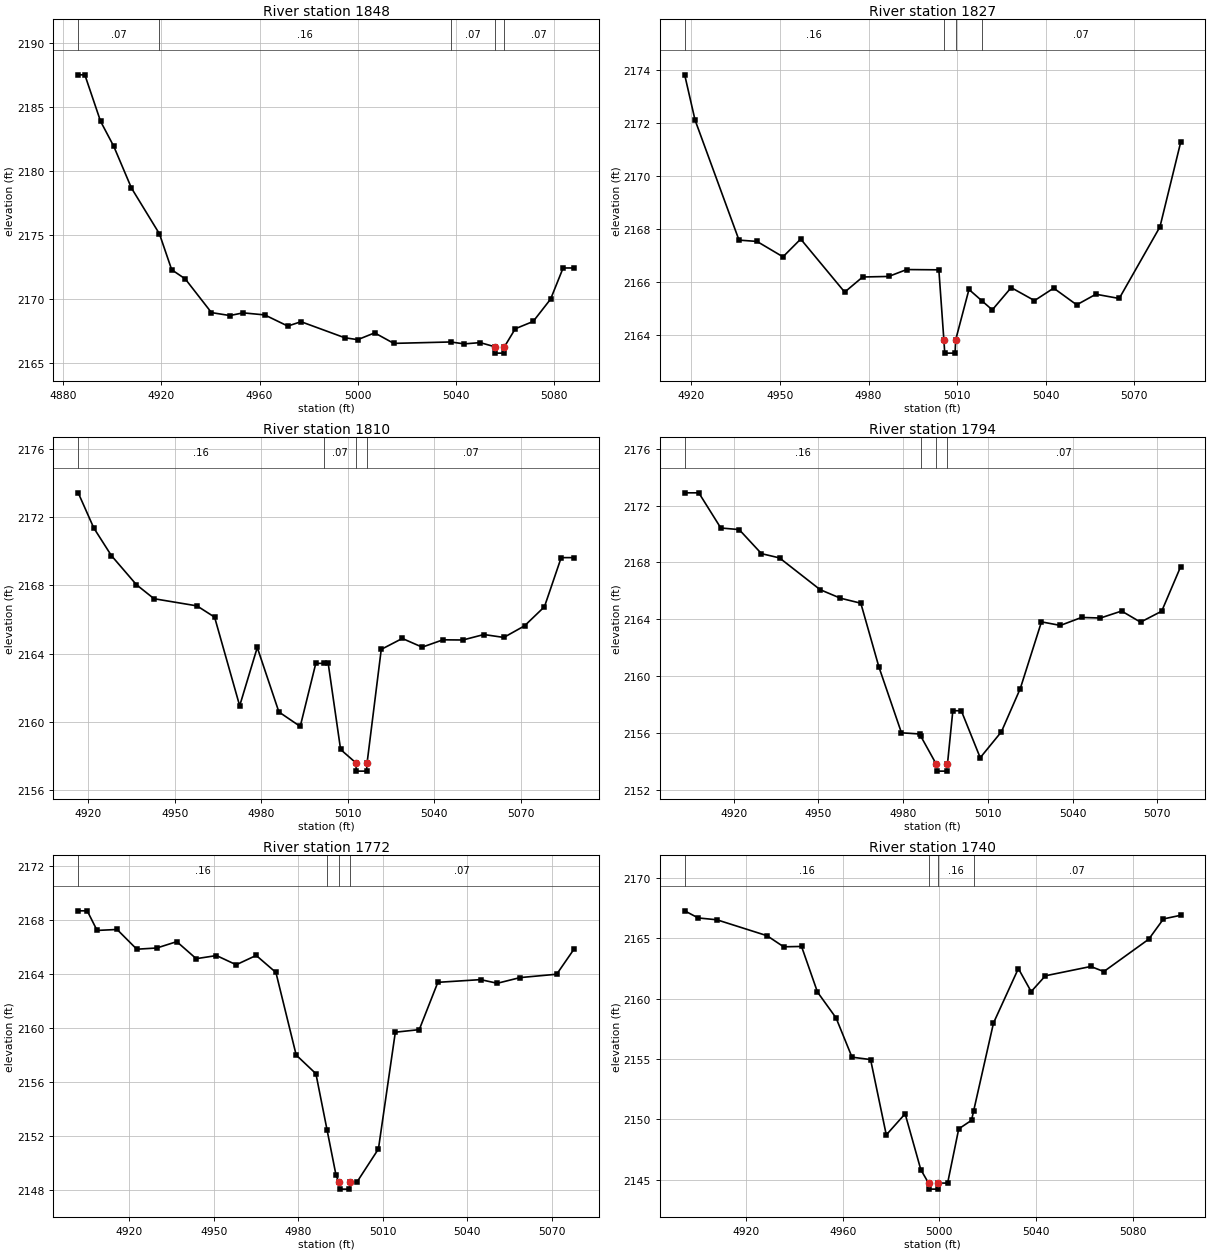
Type RM Length L Ch R = 1,1848,21,21,21
BEGIN DESCRIPTION:
Elm 63 1847.707
END DESCRIPTION:
XS GIS Cut Line= 3
      1520855.04      6769737.98      1520959.84      6769693.38
      1521027.90      6769637.27
#Sta/Elev= 30
  4886.1 2187.50  4888.8 2187.50  4895.2 2183.88  4900.6 2181.92  4907.8 2178.67
  4919.2 2175.10  4924.2 2172.30  4929.7 2171.59  4940.4 2168.96  4947.9 2168.73
  4953.3 2168.94  4962.1 2168.78  4971.5 2167.91  4976.9 2168.25  4994.7 2167.00
  5000.0 2166.85  5006.9 2167.38  5014.7 2166.56  5037.9 2166.67  5043.4 2166.52
  5049.9 2166.62  5055.8 2166.30  5056.0 2165.80  5059.5 2165.80  5059.8 2166.30
  5064.2 2167.70  5071.5 2168.27  5078.6 2170.01  5083.7 2172.44  5088.2 2172.44
#Mann=5,-1,0
  4886.1    0.07       0  4919.2    0.16       0  5037.9    0.07       0
  5055.8    0.07       0  5059.8    0.07       0
Bank Sta=5055.8,5059.8
Exp/Cntr=0.3,0.1

Type RM Length L Ch R = 1,1827,17,17,17
BEGIN DESCRIPTION:
Elm 63 1827.37
END DESCRIPTION:
XS GIS Cut Line= 3
      1520906.54      6769754.62      1520974.22      6769707.77
      1521040.39      6769653.33
#Sta/Elev= 26
  4917.7 2173.81  4921.2 2172.11  4936.1 2167.58  4942.2 2167.53  4951.0 2166.95
  4957.0 2167.62  4971.9 2165.62  4978.0 2166.19  4986.8 2166.21  4992.9 2166.47
  5003.8 2166.46  5005.5 2163.82  5005.8 2163.32  5009.3 2163.32  5009.5 2163.82
  5014.0 2165.72  5018.3 2165.30  5021.9 2164.95  5028.3 2165.79  5036.2 2165.30
  5042.7 2165.77  5050.5 2165.14  5057.0 2165.54  5064.9 2165.38  5078.7 2168.08
  5085.7 2171.26
#Mann=4,-1,0
  4917.7    0.16       0  5005.5    0.07       0  5009.5    0.16       0
  5018.3    0.07       0
Bank Sta=5005.5,5009.5
Exp/Cntr=0.3,0.1

Type RM Length L Ch R = 1,1810,16,16,16
BEGIN DESCRIPTION:
Elm 63 1810.13
END DESCRIPTION:
XS GIS Cut Line= 3
      1520917.82      6769767.65      1520988.98      6769718.19
      1521048.01      6769656.55
#Sta/Elev= 30
  4916.5 2173.43  4921.9 2171.37  4928.0 2169.75  4936.7 2168.04  4942.8 2167.22
  4957.7 2166.80  4963.8 2166.14  4972.5 2160.94  4978.6 2164.36  4986.1 2160.58
  4993.5 2159.73  4998.9 2163.43  5001.6 2163.43  5003.2 2163.43  5007.5 2158.38
  5012.7 2157.61  5013.0 2157.11  5016.5 2157.11  5016.7 2157.61  5021.6 2164.25
  5028.9 2164.89  5035.8 2164.38  5043.0 2164.81  5049.9 2164.80  5057.2 2165.12
  5064.1 2164.95  5071.3 2165.63  5078.2 2166.75  5084.0 2169.63  5088.5 2169.63
#Mann=4,-1,0
  4916.5    0.16       0  5001.6    0.07       0  5012.7    0.07       0
  5016.7    0.07       0
Bank Sta=5012.7,5016.7
Exp/Cntr=0.3,0.1

Type RM Length L Ch R = 1,1794,22,22,22
BEGIN DESCRIPTION:
Elm 63 1794.35
END DESCRIPTION:
XS GIS Cut Line= 3
      1520922.17      6769792.82      1520995.92      6769732.94
      1521049.95      6769673.00
#Sta/Elev= 30
  4902.6 2172.89  4907.6 2172.89  4915.4 2170.42  4921.9 2170.31  4929.8 2168.62
  4936.2 2168.32  4950.6 2166.09  4957.8 2165.49  4965.0 2165.14  4971.4 2160.67
  4979.4 2156.04  4985.8 2155.96  4986.2 2155.82  4991.7 2153.85  4992.0 2153.35
  4995.5 2153.35  4995.7 2153.85  4997.6 2157.59  5000.6 2157.59  5007.3 2154.29
  5014.8 2156.11  5021.5 2159.15  5029.0 2163.83  5035.7 2163.58  5043.2 2164.14
  5049.9 2164.10  5057.4 2164.59  5064.1 2163.81  5071.6 2164.58  5078.3 2167.70
#Mann=4,-1,0
  4902.6    0.16       0  4986.2    0.07       0  4991.7    0.07       0
  4995.7    0.07       0
Bank Sta=4991.7,4995.7
Exp/Cntr=0.3,0.1

Type RM Length L Ch R = 1,1772,32,32,32
BEGIN DESCRIPTION:
Elm 63 1771.66
END DESCRIPTION:
XS GIS Cut Line= 3
      1520945.58      6769818.00      1521011.55      6769750.30
      1521056.00      6769681.91
#Sta/Elev= 30
  4901.8 2168.66  4905.0 2168.66  4908.5 2167.21  4915.6 2167.28  4922.6 2165.82
  4929.7 2165.91  4936.8 2166.38  4943.7 2165.12  4950.9 2165.35  4957.9 2164.67
  4965.0 2165.36  4972.0 2164.10  4979.2 2157.99  4986.2 2156.61  4990.2 2152.41
  4993.3 2149.15  4994.3 2148.57  4994.6 2148.07  4998.1 2148.07  4998.3 2148.57
  5000.7 2148.57  5008.4 2151.04  5014.4 2159.68  5022.9 2159.87  5029.5 2163.37
  5044.7 2163.57  5050.6 2163.30  5058.7 2163.72  5071.7 2163.97  5077.9 2165.84
#Mann=4,-1,0
  4901.8    0.16       0  4990.2    0.07       0  4994.3    0.07       0
  4998.3    0.07       0
Bank Sta=4994.3,4998.3
Exp/Cntr=0.3,0.1

Type RM Length L Ch R = 1,1740,24,24,24
BEGIN DESCRIPTION:
Elm 63 1740.13
END DESCRIPTION:
XS GIS Cut Line= 3
      1520968.13      6769849.28      1521036.72      6769768.53
      1521072.30      6769675.67
#Sta/Elev= 30
  4894.5 2167.27  4900.1 2166.68  4907.8 2166.53  4928.6 2165.21  4935.5 2164.29
  4942.9 2164.32  4949.5 2160.54  4957.2 2158.40  4963.8 2155.15  4971.5 2154.95
  4978.0 2148.71  4985.8 2150.46  4992.3 2145.83  4995.5 2144.72  4995.8 2144.22
  4999.3 2144.22  4999.5 2144.72  5003.4 2144.72  5008.0 2149.21  5013.3 2149.92
  5014.2 2150.72  5022.4 2157.98  5032.7 2162.49  5038.0 2160.58  5043.9 2161.89
  5062.7 2162.66  5068.1 2162.24  5086.7 2164.92  5092.8 2166.60  5099.9 2166.90
#Mann=4,-1,0
  4894.5    0.16       0  4995.5    0.07       0  4999.5    0.16       0
  5014.2    0.07       0
Bank Sta=4995.5,4999.5
Exp/Cntr=0.3,0.1

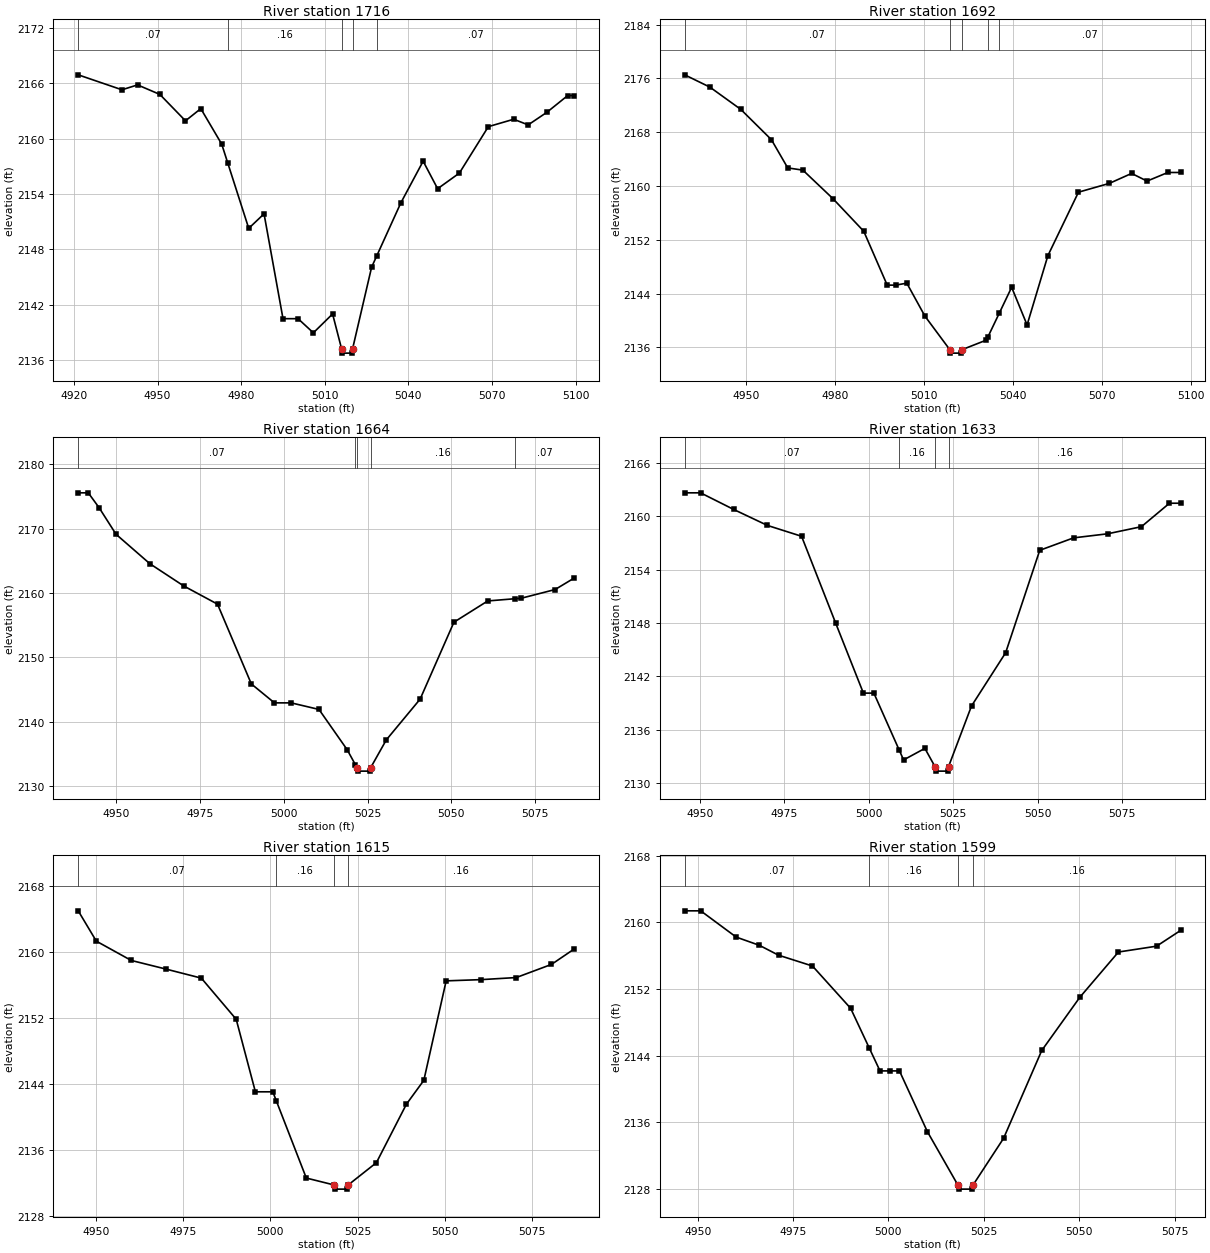
Type RM Length L Ch R = 1,1716,24,24,24
BEGIN DESCRIPTION:
Elm 63 1715.71
END DESCRIPTION:
XS GIS Cut Line= 3
      1521021.95      6769854.50      1521055.82      6769783.29
      1521085.34      6769688.64
#Sta/Elev= 30
  4921.5 2166.90  4937.2 2165.28  4942.8 2165.81  4950.8 2164.78  4960.0 2161.92
  4965.5 2163.24  4973.0 2159.40  4975.2 2157.33  4982.7 2150.28  4988.2 2151.85
  4995.0 2140.50  5000.4 2140.50  5005.9 2138.97  5012.8 2141.01  5016.0 2137.27
  5016.3 2136.77  5019.8 2136.77  5020.0 2137.27  5026.8 2146.07  5028.7 2147.33
  5037.3 2153.04  5045.3 2157.55  5050.5 2154.57  5058.3 2156.26  5068.7 2161.29
  5077.8 2162.09  5083.0 2161.48  5089.7 2162.84  5097.2 2164.66  5099.5 2164.66
#Mann=5,-1,0
  4921.5    0.07       0  4975.2    0.16       0  5016.0    0.07       0
  5020.0    0.16       0  5028.7    0.07       0
Bank Sta=5016,5020
Exp/Cntr=0.3,0.1

Type RM Length L Ch R = 1,1692,28,28,28
BEGIN DESCRIPTION:
Elm 63 1691.62
END DESCRIPTION:
XS GIS Cut Line= 3
      1521061.02      6769856.23      1521079.25      6769787.63
      1521103.56      6769694.74
#Sta/Elev= 28
  4929.4 2176.54  4937.9 2174.71  4948.3 2171.40  4958.6 2166.90  4964.1 2162.70
  4969.2 2162.37  4979.3 2158.14  4989.7 2153.28  4997.6 2145.27  5000.4 2145.27
  5004.2 2145.56  5010.3 2140.66  5018.7 2135.66  5018.9 2135.16  5022.4 2135.16
  5022.7 2135.66  5031.0 2137.10  5031.5 2137.56  5035.4 2141.16  5039.5 2144.95
  5044.7 2139.35  5051.7 2149.65  5062.0 2159.09  5072.4 2160.40  5079.9 2161.88
  5085.1 2160.74  5092.1 2162.02  5096.4 2162.02
#Mann=5,-1,0
  4929.4    0.07       0  5018.7    0.07       0  5022.7    0.07       0
  5031.5    0.16       0  5035.4    0.07       0
Bank Sta=5018.7,5022.7
Exp/Cntr=0.3,0.1

Type RM Length L Ch R = 1,1664,31,31,31
BEGIN DESCRIPTION:
Elm 63 1663.6
END DESCRIPTION:
XS GIS Cut Line= 3
      1521099.22      6769849.25      1521107.03      6769789.37
      1521118.23      6769702.37
#Sta/Elev= 25
  4938.6 2175.55  4941.6 2175.55  4944.8 2173.27  4949.9 2169.11  4960.0 2164.54
  4970.1 2161.09  4980.2 2158.26  4990.3 2145.87  4997.2 2142.93  5002.2 2142.93
  5010.5 2141.91  5018.9 2135.67  5021.4 2133.30  5021.9 2132.83  5022.2 2132.33
  5025.7 2132.33  5025.9 2132.83  5030.6 2137.18  5040.7 2143.51  5050.8 2155.46
  5060.9 2158.76  5068.9 2159.10  5070.9 2159.18  5081.0 2160.53  5086.7 2162.31
#Mann=5,-1,0
  4938.6    0.07       0  5021.4    0.16       0  5021.9    0.07       0
  5025.9    0.16       0  5068.9    0.07       0
Bank Sta=5021.9,5025.9
Exp/Cntr=0.3,0.1

Type RM Length L Ch R = 1,1633,18,18,18
BEGIN DESCRIPTION:
Elm 63 1632.66
END DESCRIPTION:
XS GIS Cut Line= 3
      1521131.33      6769842.35      1521138.28      6769786.76
      1521147.83      6769696.49
#Sta/Elev= 23
  4945.5 2162.66  4950.2 2162.66  4960.0 2160.79  4970.0 2158.99  4980.1 2157.77
  4990.2 2147.99  4998.4 2140.12  5001.5 2140.12  5009.0 2133.71  5010.3 2132.60
  5016.6 2133.90  5019.6 2131.84  5019.9 2131.34  5023.4 2131.34  5023.6 2131.84
  5030.4 2138.67  5040.5 2144.66  5050.6 2156.19  5060.6 2157.59  5070.7 2158.05
  5080.7 2158.85  5089.0 2161.49  5092.3 2161.49
#Mann=4,-1,0
  4945.5    0.07       0  5009.0    0.16       0  5019.6    0.07       0
  5023.6    0.16       0
Bank Sta=5019.6,5023.6
Exp/Cntr=0.3,0.1

Type RM Length L Ch R = 1,1615,16,16,16
BEGIN DESCRIPTION:
Elm 63 1614.76
END DESCRIPTION:
XS GIS Cut Line= 3
      1521152.17      6769843.18      1521155.64      6769791.97
      1521164.18      6769701.50
#Sta/Elev= 22
  4944.9 2164.94  4950.1 2161.27  4960.1 2158.94  4970.1 2157.89  4980.2 2156.80
  4990.2 2151.82  4995.7 2143.05  5000.7 2143.05  5001.7 2141.96  5010.3 2132.62
  5018.3 2131.78  5018.6 2131.28  5022.1 2131.28  5022.3 2131.78  5030.4 2134.48
  5039.0 2141.55  5044.0 2144.44  5050.4 2156.47  5060.5 2156.62  5070.5 2156.87
  5080.6 2158.46  5087.1 2160.32
#Mann=4,-1,0
  4944.9    0.07       0  5001.7    0.16       0  5018.3    0.07       0
  5022.3    0.16       0
Bank Sta=5018.3,5022.3
Exp/Cntr=0.3,0.1

Type RM Length L Ch R = 1,1599,31,31,31
BEGIN DESCRIPTION:
Elm 63 1598.66
END DESCRIPTION:
XS GIS Cut Line= 3
      1521168.66      6769841.46      1521172.14      6769787.63
      1521176.40      6769711.69
#Sta/Elev= 22
  4946.6 2161.37  4950.8 2161.37  4960.1 2158.22  4966.2 2157.23  4971.2 2156.05
  4980.1 2154.75  4990.1 2149.68  4995.0 2144.90  4997.8 2142.17  5000.5 2142.17
  5002.9 2142.17  5010.2 2134.90  5018.2 2128.49  5018.5 2127.99  5022.0 2127.99
  5022.2 2128.49  5030.2 2134.09  5040.2 2144.62  5050.2 2151.01  5060.3 2156.43
  5070.3 2157.13  5076.6 2159.02
#Mann=4,-1,0
  4946.6    0.07       0  4995.0    0.16       0  5018.2    0.07       0
  5022.2    0.16       0
Bank Sta=5018.2,5022.2
Exp/Cntr=0.3,0.1

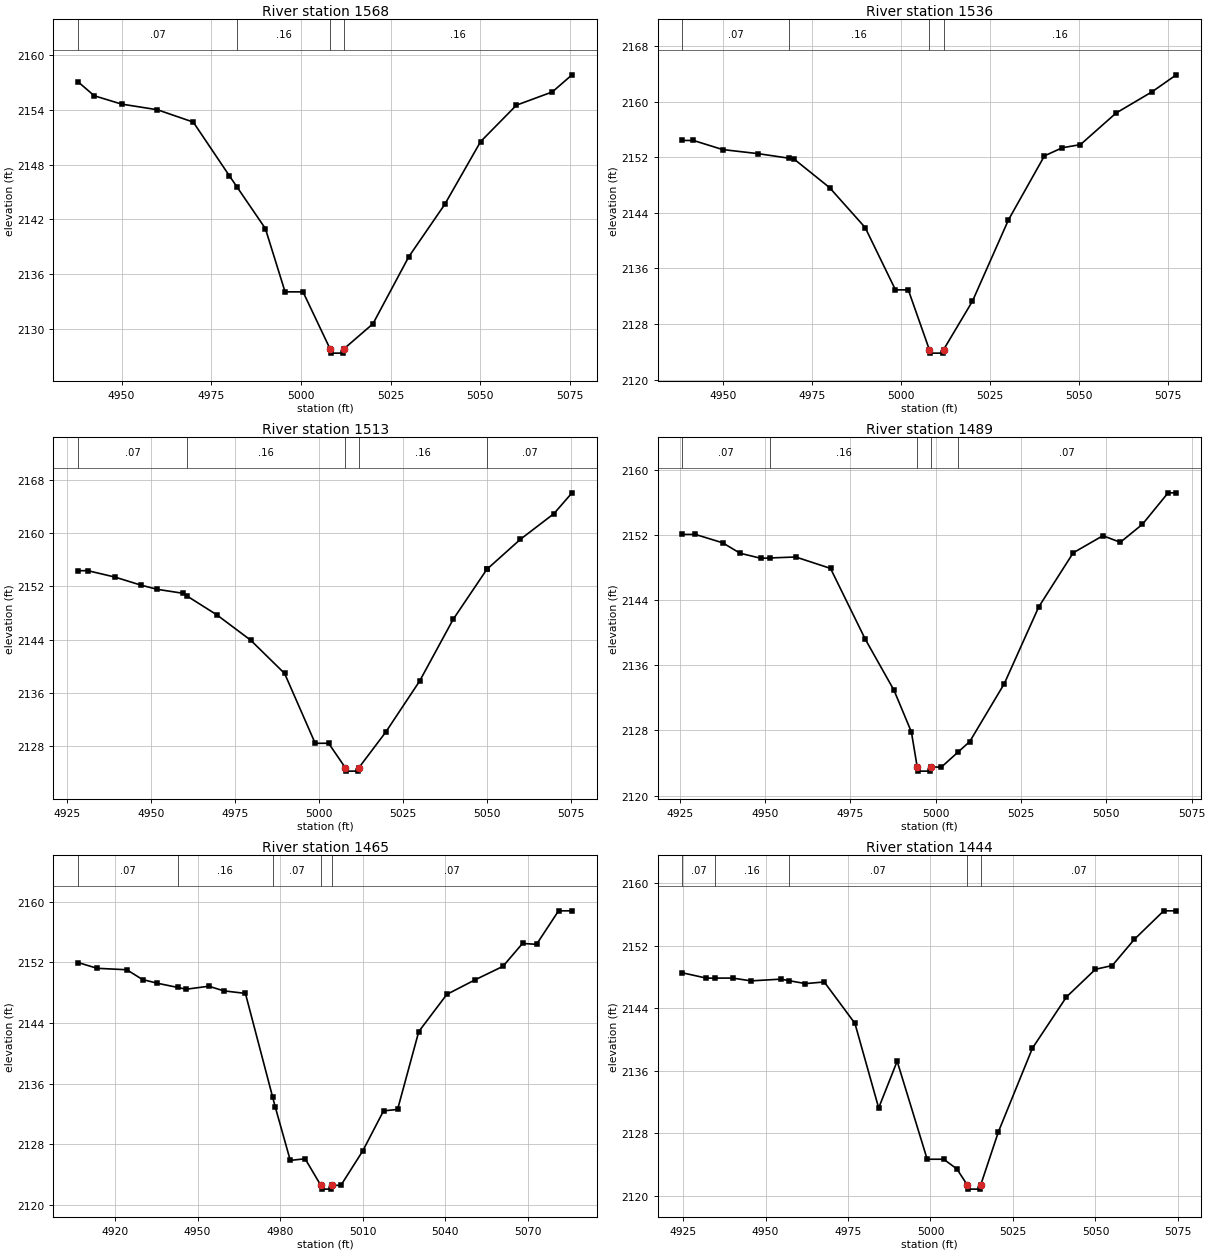
Type RM Length L Ch R = 1,1568,32,32,32
BEGIN DESCRIPTION:
Elm 63 1568.07
END DESCRIPTION:
XS GIS Cut Line= 3
      1521199.92      6769850.11      1521202.52      6769791.97
      1521205.97      6769712.55
#Sta/Elev= 21
  4937.9 2157.05  4942.4 2155.53  4950.0 2154.62  4960.0 2154.00  4970.0 2152.65
  4980.1 2146.76  4982.2 2145.55  4990.1 2141.01  4995.6 2134.08  5000.6 2134.08
  5008.1 2127.88  5008.3 2127.38  5011.8 2127.38  5012.1 2127.88  5020.1 2130.59
  5030.1 2137.93  5040.1 2143.64  5050.1 2150.51  5060.1 2154.50  5070.1 2155.95
  5075.6 2157.82
#Mann=4,-1,0
  4937.9    0.07       0  4982.2    0.16       0  5008.1    0.07       0
  5012.1    0.16       0
Bank Sta=5008.1,5012.1
Exp/Cntr=0.3,0.1

Type RM Length L Ch R = 1,1536,23,23,23
BEGIN DESCRIPTION:
Elm 63 1536.18
END DESCRIPTION:
XS GIS Cut Line= 3
      1521232.90      6769849.26      1521234.64      6769785.89
      1521243.97      6769711.26
#Sta/Elev= 22
  4938.7 2154.41  4941.8 2154.41  4950.0 2153.10  4960.0 2152.51  4968.7 2151.85
  4970.0 2151.75  4980.0 2147.63  4990.0 2141.88  4998.5 2132.92  5002.1 2132.92
  5008.0 2124.32  5008.3 2123.82  5011.8 2123.82  5012.0 2124.32  5020.1 2131.29
  5030.2 2142.98  5040.3 2152.19  5045.3 2153.36  5050.4 2153.81  5060.4 2158.35
  5070.5 2161.41  5077.3 2163.85
#Mann=4,-1,0
  4938.7    0.07       0  4968.7    0.16       0  5008.0    0.07       0
  5012.0    0.16       0
Bank Sta=5008,5012
Exp/Cntr=0.3,0.1

Type RM Length L Ch R = 1,1513,24,24,24
BEGIN DESCRIPTION:
Elm 63 1513.12
END DESCRIPTION:
XS GIS Cut Line= 3
      1521246.79      6769858.79      1521258.07      6769785.03
      1521259.80      6769712.56
#Sta/Elev= 24
  4928.3 2154.36  4931.2 2154.36  4939.2 2153.41  4946.9 2152.21  4951.9 2151.56
  4959.4 2150.98  4960.7 2150.57  4969.6 2147.74  4979.7 2143.93  4989.8 2138.94
  4998.9 2128.47  5002.9 2128.47  5007.9 2124.79  5008.2 2124.29  5011.7 2124.29
  5011.9 2124.79  5019.9 2130.13  5030.0 2137.79  5040.0 2147.06  5050.0 2154.54
  5050.1 2154.59  5060.0 2159.06  5070.0 2162.91  5075.4 2166.04
#Mann=5,-1,0
  4928.3    0.07       0  4960.7    0.16       0  5007.9    0.07       0
  5011.9    0.16       0  5050.1    0.07       0
Bank Sta=5007.9,5011.9
Exp/Cntr=0.3,0.1

Type RM Length L Ch R = 1,1489,24,24,24
BEGIN DESCRIPTION:
Elm 63 1489
END DESCRIPTION:
XS GIS Cut Line= 3
      1521266.76      6769860.51      1521281.51      6769789.37
      1521292.79      6769718.21
#Sta/Elev= 26
  4925.8 2152.05  4929.6 2152.05  4937.6 2151.02  4942.7 2149.74  4948.8 2149.12
  4951.5 2149.16  4959.0 2149.28  4969.2 2147.88  4979.4 2139.18  4987.8 2132.93
  4992.9 2127.81  4994.6 2123.51  4994.8 2123.01  4998.3 2123.01  4998.6 2123.51
  5001.7 2123.51  5006.5 2125.32  5010.0 2126.64  5020.1 2133.73  5030.2 2143.15
  5040.3 2149.79  5049.0 2151.89  5054.1 2151.08  5060.6 2153.30  5068.1 2157.15
  5070.5 2157.15
#Mann=5,-1,0
  4925.8    0.07       0  4951.5    0.16       0  4994.6    0.07       0
  4998.6    0.16       0  5006.5    0.07       0
Bank Sta=4994.6,4998.6
Exp/Cntr=0.3,0.1

Type RM Length L Ch R = 1,1465,21,21,21
BEGIN DESCRIPTION:
Elm 63 1464.79
END DESCRIPTION:
XS GIS Cut Line= 3
      1521271.11      6769874.40      1521305.82      6769788.50
      1521323.18      6769703.40
#Sta/Elev= 30
  4906.6 2151.98  4913.5 2151.22  4924.3 2151.03  4930.0 2149.74  4935.4 2149.25
  4942.9 2148.69  4945.9 2148.46  4954.1 2148.86  4959.5 2148.25  4967.4 2147.91
  4977.3 2134.23  4978.2 2132.99  4983.7 2125.89  4989.1 2126.10  4994.8 2122.60
  4995.1 2122.10  4998.6 2122.10  4998.8 2122.60  5002.1 2122.60  5010.0 2127.11
  5017.6 2132.42  5022.7 2132.61  5030.4 2142.88  5040.6 2147.78  5050.8 2149.69
  5061.0 2151.48  5068.1 2154.50  5073.2 2154.38  5081.2 2158.80  5086.1 2158.80
#Mann=5,-1,0
  4906.6    0.07       0  4942.9    0.16       0  4977.3    0.07       0
  4994.8    0.07       0  4998.8    0.07       0
Bank Sta=4994.8,4998.8
Exp/Cntr=0.3,0.1

Type RM Length L Ch R = 1,1444,19,19,19
BEGIN DESCRIPTION:
Elm 63 1444.21
END DESCRIPTION:
XS GIS Cut Line= 3
      1521291.93      6769854.46      1521328.39      6769784.16
      1521344.87      6769715.60
#Sta/Elev= 27
  4924.8 2148.53  4932.1 2147.85  4934.7 2147.85  4940.0 2147.86  4945.6 2147.50
  4954.6 2147.72  4957.1 2147.53  4962.1 2147.15  4967.8 2147.36  4977.1 2142.07
  4984.3 2131.26  4989.9 2137.23  4999.0 2124.71  5004.0 2124.71  5008.0 2123.47
  5011.2 2121.39  5011.4 2120.89  5014.9 2120.89  5015.2 2121.39  5020.6 2128.23
  5030.9 2138.90  5041.2 2145.44  5050.0 2148.98  5055.1 2149.46  5061.8 2152.81
  5070.7 2156.45  5074.5 2156.45
#Mann=5,-1,0
  4924.8    0.07       0  4934.7    0.16       0  4957.1    0.07       0
  5011.2    0.07       0  5015.2    0.07       0
Bank Sta=5011.2,5015.2
Exp/Cntr=0.3,0.1

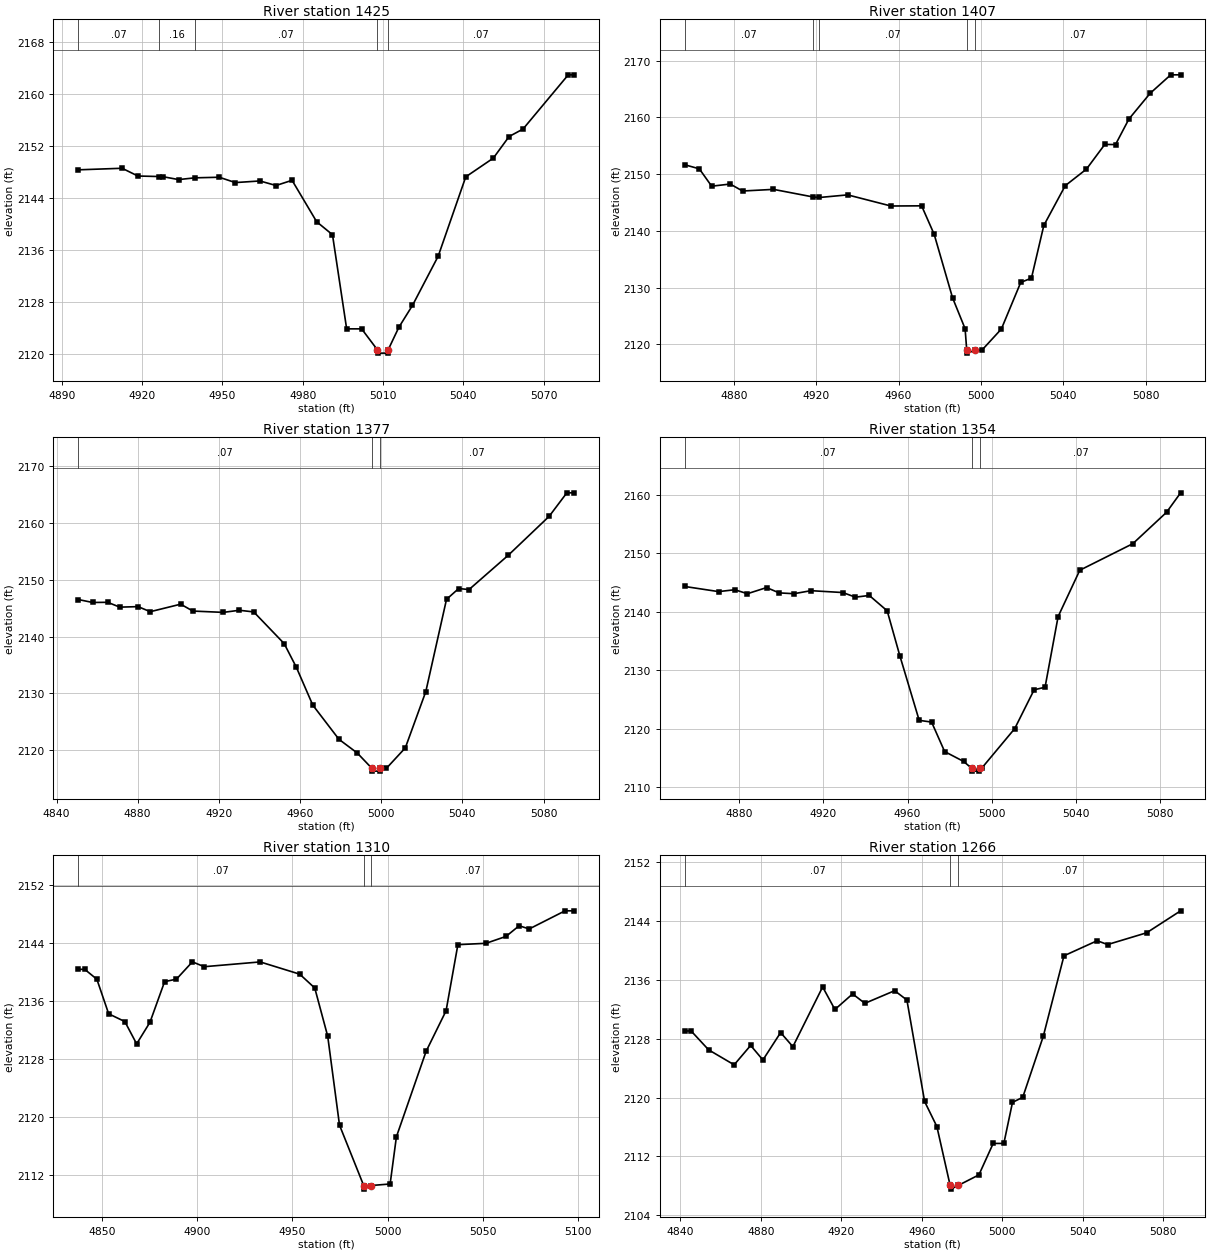
Type RM Length L Ch R = 1,1425,18,18,18
BEGIN DESCRIPTION:
Elm 63 1424.8
END DESCRIPTION:
XS GIS Cut Line= 3
      1521290.22      6769875.27      1521345.75      6769788.50
      1521365.70      6769708.67
#Sta/Elev= 29
  4896.1 2148.29  4912.5 2148.53  4918.4 2147.34  4926.3 2147.26  4927.7 2147.24
  4933.6 2146.79  4939.7 2147.06  4948.8 2147.15  4954.8 2146.33  4964.0 2146.58
  4970.0 2145.88  4976.0 2146.68  4985.2 2140.31  4991.1 2138.32  4996.4 2123.85
  5002.0 2123.85  5007.9 2120.62  5008.2 2120.12  5011.7 2120.12  5011.9 2120.62
  5015.9 2124.09  5021.0 2127.46  5030.6 2135.02  5040.9 2147.21  5051.2 2150.09
  5057.1 2153.41  5062.3 2154.56  5079.2 2162.89  5081.4 2162.89
#Mann=5,-1,0
  4896.1    0.07       0  4926.3    0.16       0  4939.7    0.07       0
  5007.9    0.07       0  5011.9    0.07       0
Bank Sta=5007.9,5011.9
Exp/Cntr=0.3,0.1

Type RM Length L Ch R = 1,1407,30,30,30
BEGIN DESCRIPTION:
Elm 63 1406.59
END DESCRIPTION:
XS GIS Cut Line= 3
      1521285.09      6769907.43      1521363.22      6769791.32
      1521388.16      6769693.71
#Sta/Elev= 30
  4856.2 2151.65  4863.3 2150.93  4869.3 2147.87  4878.3 2148.25  4884.3 2147.02
  4899.3 2147.31  4918.7 2145.96  4921.6 2145.88  4935.3 2146.34  4956.3 2144.38
  4971.2 2144.41  4977.3 2139.38  4986.2 2128.22  4992.3 2122.76  4993.1 2118.96
  4993.4 2118.46  4997.1 2118.96  5000.4 2118.96  5009.9 2122.71  5019.3 2130.92
  5024.5 2131.67  5030.5 2140.95  5040.9 2147.96  5051.2 2150.88  5060.1 2155.23
  5065.3 2155.20  5071.8 2159.70  5082.1 2164.23  5092.1 2167.49  5096.9 2167.49
#Mann=5,-1,0
  4856.2    0.07       0  4918.7    0.16       0  4921.6    0.07       0
  4993.1    0.07       0  4997.1    0.07       0
Bank Sta=4993.1,4997.1
Exp/Cntr=0.3,0.1

Type RM Length L Ch R = 1,1377,23,23,23
BEGIN DESCRIPTION:
Elm 63 1376.81
END DESCRIPTION:
XS GIS Cut Line= 3
      1521311.15      6769913.91      1521393.60      6769791.32
      1521408.79      6769695.85
#Sta/Elev= 30
  4850.7 2146.51  4857.8 2145.99  4865.2 2146.02  4871.2 2145.17  4880.2 2145.26
  4886.2 2144.37  4901.2 2145.69  4907.2 2144.48  4922.2 2144.25  4930.1 2144.62
  4937.2 2144.33  4952.2 2138.76  4958.2 2134.60  4966.3 2127.95  4979.2 2121.94
  4988.2 2119.54  4995.4 2116.85  4995.7 2116.35  4999.2 2116.35  4999.4 2116.85
  5002.6 2116.85  5011.9 2120.44  5022.0 2130.34  5032.2 2146.54  5038.2 2148.44
  5043.3 2148.26  5062.6 2154.28  5082.8 2161.14  5091.5 2165.26  5095.1 2165.26
#Mann=3,-1,0
  4850.7    0.07       0  4995.4    0.07       0  4999.4    0.07       0
Bank Sta=4995.4,4999.4
Exp/Cntr=0.3,0.1

Type RM Length L Ch R = 1,1354,44,44,44
BEGIN DESCRIPTION:
Elm 63 1354.22
END DESCRIPTION:
XS GIS Cut Line= 3
      1521336.10      6769921.52      1521413.13      6769803.26
      1521435.54      6769711.49
#Sta/Elev= 30
  4854.1 2144.34  4870.2 2143.46  4877.9 2143.78  4883.9 2143.10  4893.0 2144.15
  4899.0 2143.24  4906.0 2143.10  4914.1 2143.62  4929.2 2143.30  4935.2 2142.51
  4941.8 2142.80  4950.3 2140.17  4956.3 2132.49  4965.5 2121.41  4971.4 2121.11
  4977.6 2116.06  4986.6 2114.37  4990.4 2113.21  4990.6 2112.71  4994.1 2112.71
  4994.4 2113.21  4995.2 2113.21  5010.9 2120.00  5020.1 2126.64  5025.3 2127.08
  5031.5 2139.18  5041.8 2147.12  5067.0 2151.67  5083.0 2157.04  5089.7 2160.38
#Mann=3,-1,0
  4854.1    0.07       0  4990.4    0.07       0  4994.4    0.07       0
Bank Sta=4990.4,4994.4
Exp/Cntr=0.3,0.1

Type RM Length L Ch R = 1,1310,44,44,44
BEGIN DESCRIPTION:
Elm 63 1309.94
END DESCRIPTION:
XS GIS Cut Line= 3
      1521352.36      6769958.43      1521448.94      6769826.04
      1521478.22      6769733.85
#Sta/Elev= 30
  4837.4 2140.35  4840.8 2140.35  4847.2 2138.98  4853.4 2134.21  4861.9 2133.14
  4868.1 2130.06  4875.1 2133.04  4882.8 2138.65  4889.0 2138.99  4897.4 2141.38
  4903.6 2140.71  4933.0 2141.37  4953.8 2139.68  4961.7 2137.77  4968.5 2131.12
  4974.7 2118.85  4987.4 2110.52  4987.6 2110.02  4991.4 2110.52  5001.3 2110.73
  5004.6 2117.24  5020.2 2129.03  5030.7 2134.63  5036.9 2143.75  5051.7 2143.94
  5062.2 2144.89  5069.1 2146.36  5074.4 2145.92  5093.2 2148.42  5098.0 2148.42
#Mann=3,-1,0
  4837.4    0.07       0  4987.4    0.07       0  4991.4    0.07       0
Bank Sta=4987.4,4991.4
Exp/Cntr=0.3,0.1

Type RM Length L Ch R = 1,1266,64,64,64
BEGIN DESCRIPTION:
Elm 63 1266.4
END DESCRIPTION:
XS GIS Cut Line= 3
      1521400.09      6769968.21      1521488.00      6769841.23
      1521509.35      6769751.58
#Sta/Elev= 30
  4842.1 2129.06  4845.3 2129.06  4854.0 2126.49  4866.7 2124.45  4874.9 2127.09
  4881.0 2125.11  4889.8 2128.84  4895.9 2126.92  4910.7 2135.05  4916.8 2131.98
  4925.6 2134.10  4931.7 2132.82  4946.5 2134.54  4952.6 2133.27  4961.4 2119.46
  4967.5 2116.05  4974.1 2108.03  4974.4 2107.53  4978.1 2108.03  4988.4 2109.47
  4995.5 2113.75  5000.8 2113.75  5005.1 2119.34  5010.2 2120.03  5020.4 2128.32
  5030.7 2139.29  5047.2 2141.34  5052.4 2140.82  5071.8 2142.42  5088.7 2145.41
#Mann=3,-1,0
  4842.1    0.07       0  4974.1    0.07       0  4978.1    0.07       0
Bank Sta=4974.1,4978.1
Exp/Cntr=0.3,0.1