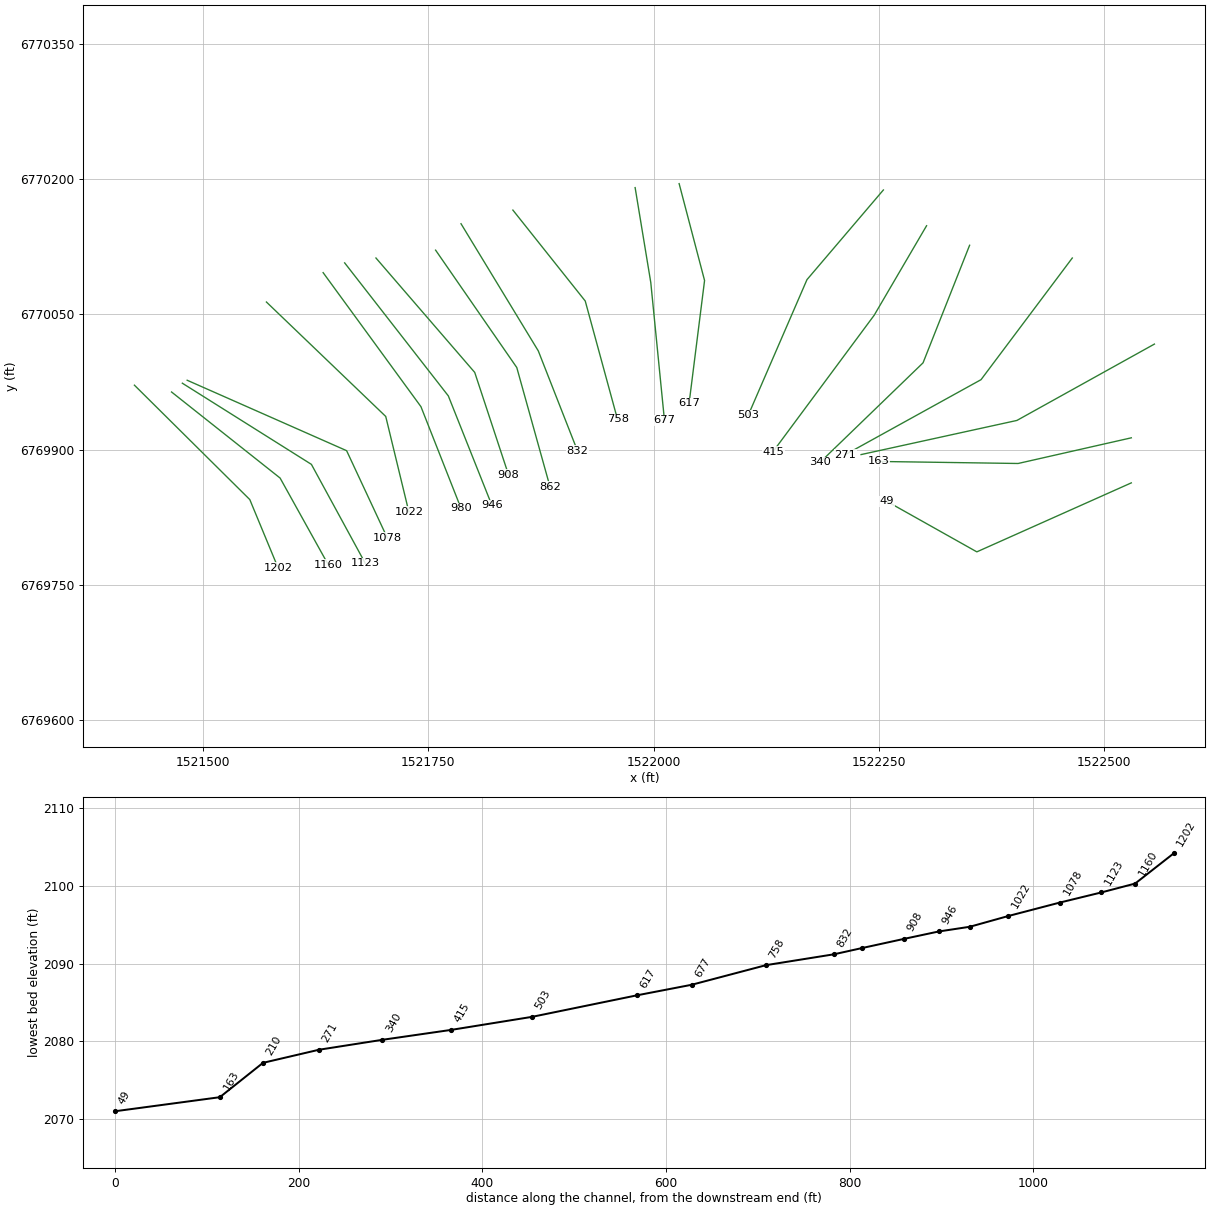
HEC-RAS study Elm 63.prj: Elm 63 Base Level Engineering

--- Elm 63.g01 (geometry) --- (continued)

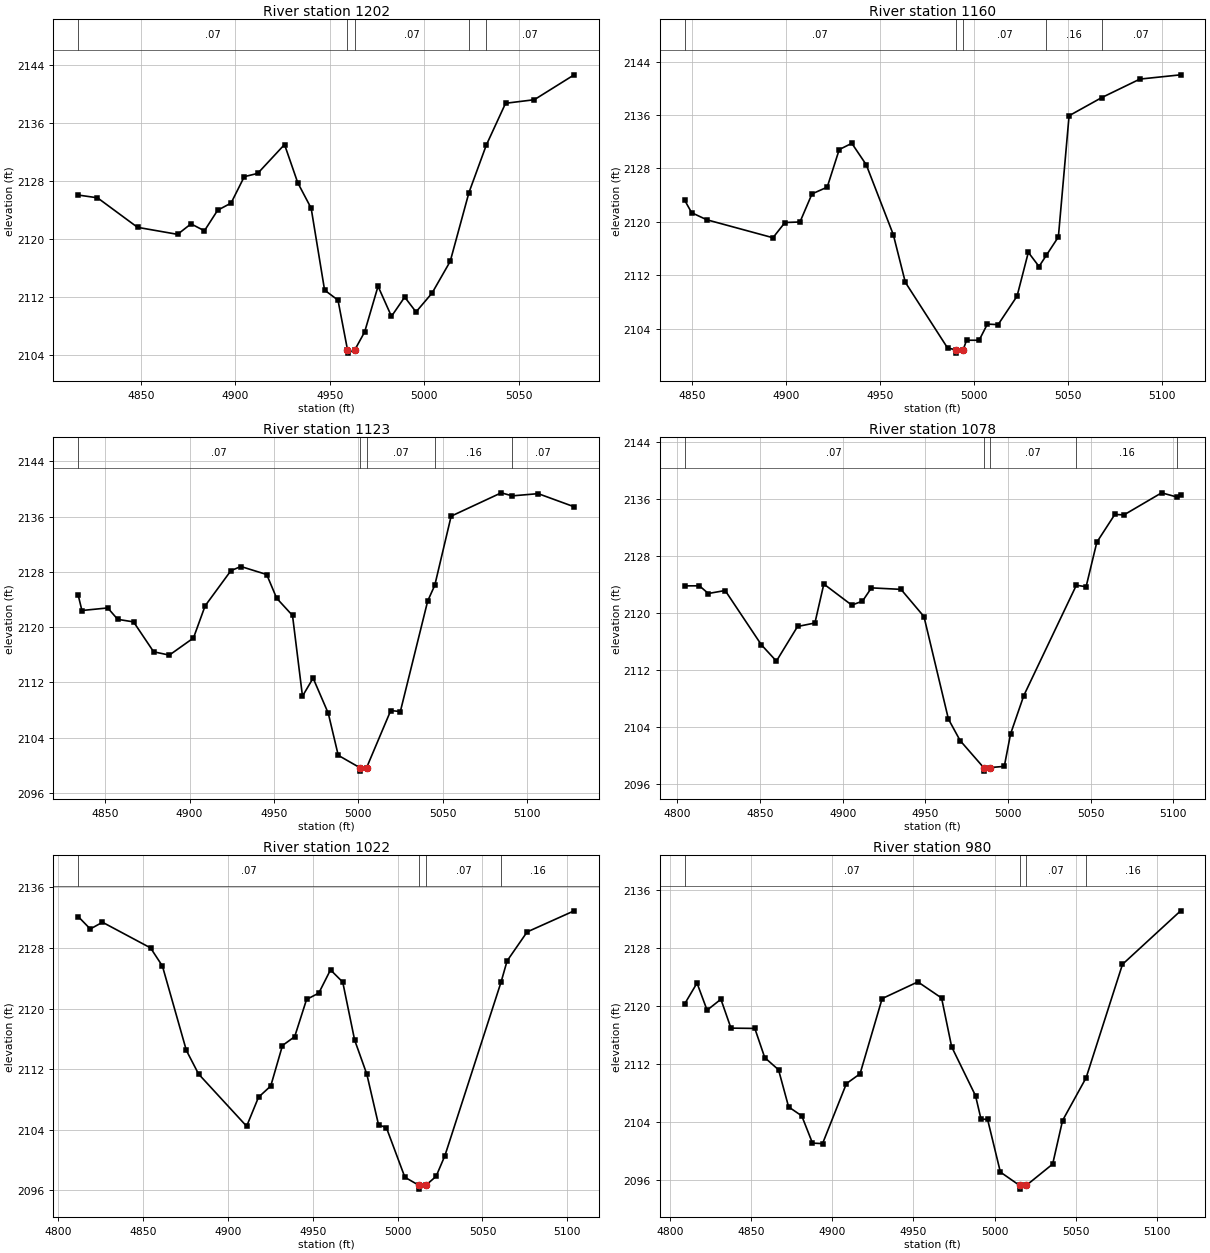
Type RM Length L Ch R = 1,1202,42,42,42
BEGIN DESCRIPTION:
Elm 63 1201.71
END DESCRIPTION:
XS GIS Cut Line= 3
      1521424.01      6769971.41      1521552.02      6769844.49
      1521583.50      6769768.51
#Sta/Elev= 30
  4816.8 2126.04  4827.0 2125.66  4848.2 2121.58  4869.4 2120.61  4876.5 2122.06
  4883.6 2121.10  4890.6 2123.94  4897.7 2124.93  4904.7 2128.58  4911.8 2129.03
  4926.0 2133.02  4933.0 2127.74  4940.1 2124.22  4947.2 2112.91  4954.3 2111.52
  4959.3 2104.70  4959.6 2104.20  4963.3 2104.70  4968.4 2107.12  4975.5 2113.44
  4982.6 2109.28  4989.6 2111.94  4995.6 2109.89  5004.1 2112.50  5013.7 2116.88
  5023.6 2126.37  5032.8 2132.94  5043.0 2138.72  5058.2 2139.21  5079.3 2142.65
#Mann=5,-1,0
  4816.8    0.07       0  4959.3    0.07       0  4963.3    0.07       0
  5023.6    0.16       0  5032.8    0.07       0
Bank Sta=4959.3,4963.3
Exp/Cntr=0.3,0.1

Type RM Length L Ch R = 1,1160,37,37,37
BEGIN DESCRIPTION:
Elm 63 1159.73
END DESCRIPTION:
XS GIS Cut Line= 3
      1521465.22      6769963.84      1521585.66      6769868.36
      1521639.28      6769771.85
#Sta/Elev= 30
  4846.0 2123.22  4849.7 2121.35  4857.8 2120.29  4893.0 2117.60  4899.4 2119.88
  4907.4 2119.96  4913.8 2124.17  4921.9 2125.18  4928.3 2130.81  4935.0 2131.75
  4942.7 2128.53  4957.1 2118.06  4963.5 2110.92  4986.0 2101.08  4990.3 2100.81
  4990.6 2100.31  4994.3 2100.81  4996.1 2102.24  5002.8 2102.24  5007.2 2104.66
  5012.9 2104.58  5023.0 2108.85  5029.0 2115.41  5034.7 2113.29  5038.6 2114.97
  5045.0 2117.72  5050.7 2135.88  5068.1 2138.60  5088.4 2141.37  5110.1 2142.01
#Mann=5,-1,0
  4846.0    0.07       0  4990.3    0.07       0  4994.3    0.07       0
  5038.6    0.16       0  5068.1    0.07       0
Bank Sta=4990.3,4994.3
Exp/Cntr=0.3,0.1

Type RM Length L Ch R = 1,1123,45,45,45
BEGIN DESCRIPTION:
Elm 63 1122.57
END DESCRIPTION:
XS GIS Cut Line= 3
      1521477.19      6769973.59      1521620.38      6769883.55
      1521680.04      6769773.99
#Sta/Elev= 30
  4834.0 2124.63  4836.2 2122.42  4851.5 2122.79  4857.4 2121.14  4866.8 2120.77
  4878.7 2116.44  4888.0 2115.96  4902.3 2118.44  4909.2 2123.09  4924.5 2128.19
  4930.4 2128.79  4945.7 2127.63  4951.6 2124.20  4961.0 2121.70  4966.9 2110.01
  4973.2 2112.63  4982.2 2107.53  4988.1 2101.45  5000.9 2099.66  5001.2 2099.16
  5004.9 2099.66  5019.2 2107.93  5024.9 2107.79  5041.1 2123.79  5045.3 2126.07
  5055.0 2136.08  5084.7 2139.46  5091.2 2139.02  5106.6 2139.34  5127.9 2137.44
#Mann=5,-1,0
  4834.0    0.07       0  5000.9    0.07       0  5004.9    0.07       0
  5045.3    0.16       0  5091.2    0.07       0
Bank Sta=5000.9,5004.9
Exp/Cntr=0.3,0.1

Type RM Length L Ch R = 1,1078,56,56,56
BEGIN DESCRIPTION:
Elm 63 1077.96
END DESCRIPTION:
XS GIS Cut Line= 3
      1521482.56      6769976.87      1521659.44      6769898.74
      1521704.57      6769802.03
#Sta/Elev= 30
  4804.4 2123.86  4813.3 2123.87  4818.7 2122.79  4828.9 2123.21  4850.8 2115.59
  4859.9 2113.30  4872.7 2118.16  4883.2 2118.65  4888.6 2124.12  4905.5 2121.16
  4912.0 2121.72  4917.4 2123.58  4935.3 2123.37  4949.2 2119.55  4964.0 2105.16
  4971.1 2102.14  4985.3 2098.36  4985.6 2097.86  4989.3 2098.36  4997.8 2098.53
  5001.6 2103.08  5009.6 2108.46  5041.4 2123.95  5047.3 2123.74  5053.8 2129.99
  5064.7 2133.89  5070.2 2133.82  5093.0 2136.92  5102.3 2136.33  5104.5 2136.56
#Mann=5,-1,0
  4804.4    0.07       0  4985.3    0.07       0  4989.3    0.07       0
  5041.4    0.16       0  5102.3    0.07       0
Bank Sta=4985.3,4989.3
Exp/Cntr=0.3,0.1

Type RM Length L Ch R = 1,1022,42,42,42
BEGIN DESCRIPTION:
Elm 63 1021.67
END DESCRIPTION:
XS GIS Cut Line= 3
      1521570.46      6770063.68      1521702.84      6769936.72
      1521728.45      6769831.10
#Sta/Elev= 30
  4811.9 2132.15  4819.0 2130.51  4826.2 2131.40  4854.5 2128.01  4861.5 2125.61
  4875.6 2114.46  4882.8 2111.34  4911.1 2104.44  4918.1 2108.28  4925.3 2109.76
  4932.2 2115.11  4939.4 2116.28  4946.4 2121.20  4953.6 2122.04  4960.5 2125.11
  4967.7 2123.49  4974.7 2115.84  4981.9 2111.31  4988.8 2104.62  4993.4 2104.26
  5004.3 2097.70  5012.6 2096.63  5012.8 2096.13  5016.6 2096.63  5022.7 2097.82
  5027.9 2100.57  5061.0 2123.53  5064.5 2126.29  5076.3 2130.12  5104.0 2132.91
#Mann=4,-1,0
  4811.9    0.07       0  5012.6    0.07       0  5016.6    0.07       0
  5061.0    0.16       0
Bank Sta=5012.6,5016.6
Exp/Cntr=0.3,0.1

Type RM Length L Ch R = 1,980,34,34,34
BEGIN DESCRIPTION:
Elm 63 980.21
END DESCRIPTION:
XS GIS Cut Line= 3
      1521633.38      6770096.25      1521741.91      6769947.57
      1521786.40      6769834.70
#Sta/Elev= 30
  4809.1 2120.26  4816.7 2123.13  4822.9 2119.39  4831.4 2120.90  4837.6 2116.92
  4852.3 2116.88  4858.4 2112.86  4866.9 2111.18  4873.1 2106.07  4881.2 2104.83
  4887.8 2101.08  4894.0 2101.01  4908.7 2109.28  4917.1 2110.63  4930.7 2120.99
  4952.7 2123.29  4967.3 2121.07  4973.5 2114.35  4988.2 2107.61  4991.6 2104.37
  4995.6 2104.37  5003.5 2097.09  5015.4 2095.24  5015.7 2094.74  5019.4 2095.24
  5035.7 2098.19  5041.8 2104.19  5056.3 2110.08  5078.7 2125.71  5114.5 2133.08
#Mann=4,-1,0
  4809.1    0.07       0  5015.4    0.07       0  5019.4    0.07       0
  5056.3    0.16       0
Bank Sta=5015.4,5019.4
Exp/Cntr=0.3,0.1

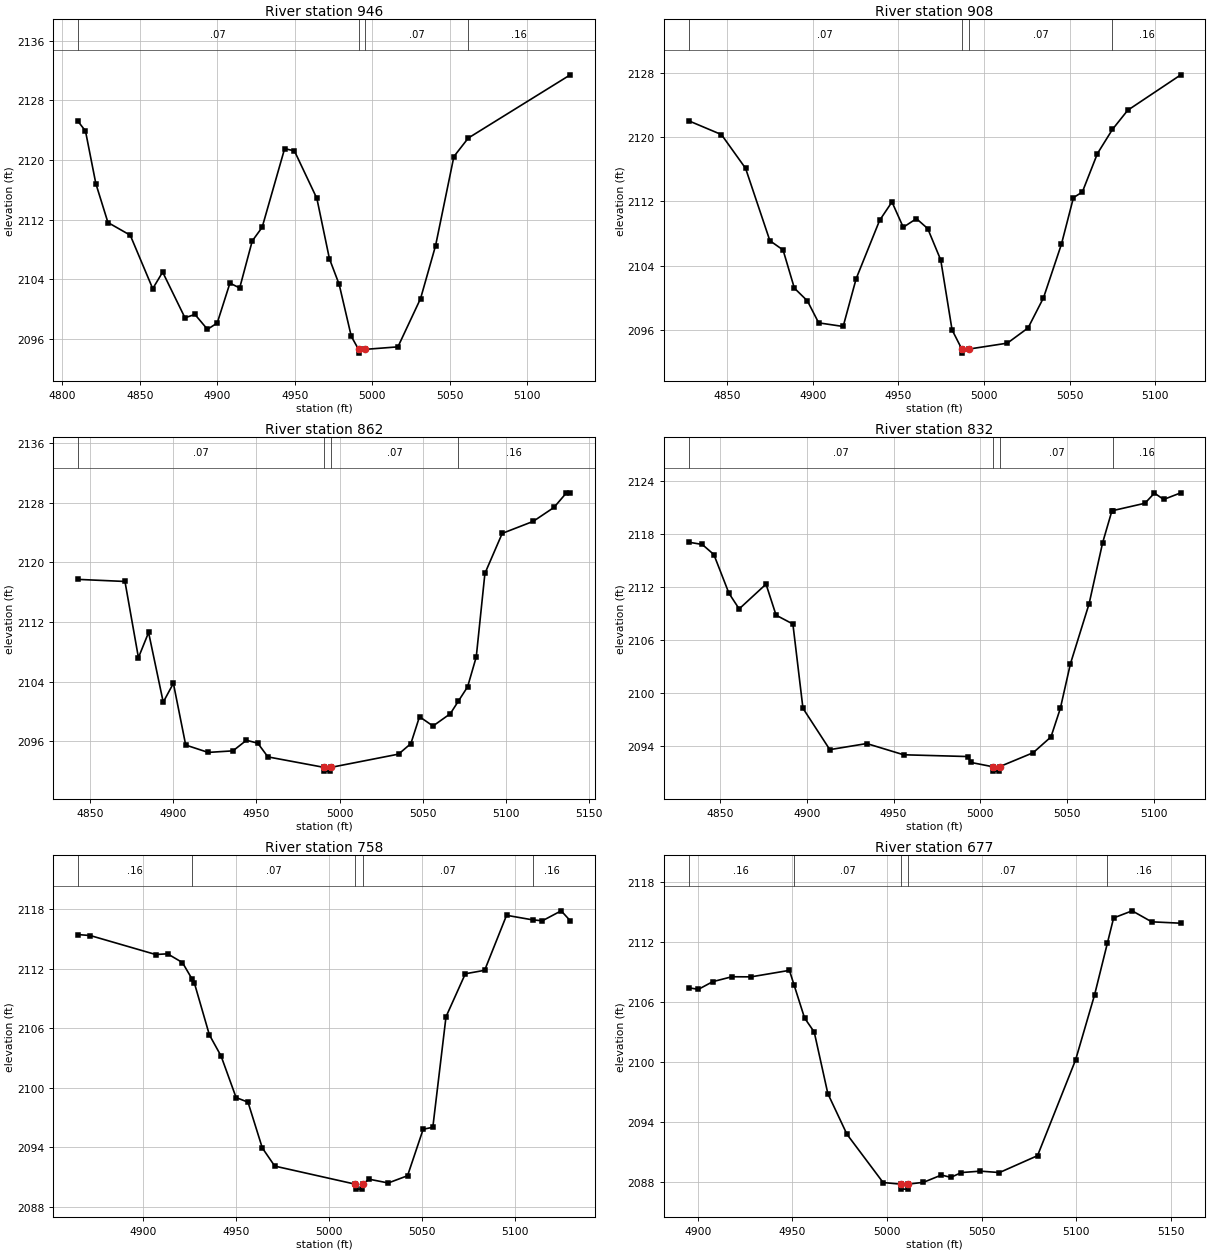
Type RM Length L Ch R = 1,946,38,38,38
BEGIN DESCRIPTION:
Elm 63 946.48
END DESCRIPTION:
XS GIS Cut Line= 3
      1521657.28      6770107.07      1521772.29      6769959.51
      1521820.57      6769838.26
#Sta/Elev= 30
  4810.2 2125.18  4815.0 2123.90  4821.7 2116.84  4829.5 2111.63  4843.9 2109.93
  4858.4 2102.77  4864.8 2104.99  4879.2 2098.86  4885.6 2099.32  4893.7 2097.32
  4900.0 2098.16  4908.2 2103.51  4914.5 2102.86  4922.6 2109.16  4929.0 2110.99
  4943.5 2121.53  4949.8 2121.23  4964.3 2114.86  4972.4 2106.78  4978.7 2103.33
  4986.5 2096.38  4991.2 2094.63  4991.5 2094.13  4995.2 2094.63  5016.6 2094.97
  5031.2 2101.44  5040.9 2108.54  5052.7 2120.47  5062.0 2122.95  5127.8 2131.42
#Mann=4,-1,0
  4810.2    0.07       0  4991.2    0.07       0  4995.2    0.07       0
  5062.0    0.16       0
Bank Sta=4991.2,4995.2
Exp/Cntr=0.3,0.1

Type RM Length L Ch R = 1,908,46,46,46
BEGIN DESCRIPTION:
Elm 63 908.24
END DESCRIPTION:
XS GIS Cut Line= 3
      1521691.99      6770112.50      1521801.59      6769985.55
      1521839.14      6769871.80
#Sta/Elev= 30
  4827.4 2122.03  4846.6 2120.31  4860.7 2116.12  4874.9 2107.13  4882.6 2105.98
  4889.2 2101.24  4896.8 2099.66  4903.4 2096.93  4917.7 2096.48  4925.3 2102.42
  4939.0 2109.66  4946.2 2111.94  4952.8 2108.80  4960.5 2109.87  4967.1 2108.63
  4974.7 2104.73  4981.3 2096.06  4987.0 2093.67  4987.2 2093.17  4991.0 2093.67
  5013.6 2094.41  5025.7 2096.30  5034.7 2100.04  5045.2 2106.71  5052.2 2112.48
  5057.4 2113.18  5066.2 2117.95  5075.0 2120.96  5083.9 2123.33  5114.9 2127.73
#Mann=4,-1,0
  4827.4    0.07       0  4987.0    0.07       0  4991.0    0.07       0
  5075.0    0.16       0
Bank Sta=4987,4991
Exp/Cntr=0.3,0.1

Type RM Length L Ch R = 1,862,30,30,30
BEGIN DESCRIPTION:
Elm 63 861.95
END DESCRIPTION:
XS GIS Cut Line= 3
      1521758.16      6770121.21      1521848.24      6769990.97
      1521885.14      6769858.57
#Sta/Elev= 30
  4842.8 2117.70  4871.0 2117.42  4879.1 2107.20  4885.2 2110.58  4894.0 2101.23
  4900.1 2103.76  4907.5 2095.48  4921.0 2094.49  4935.9 2094.70  4944.0 2096.12
  4950.8 2095.73  4956.9 2093.89  4990.7 2092.48  4990.9 2091.98  4994.4 2091.98
  4994.7 2092.48  5035.4 2094.26  5042.8 2095.67  5048.0 2099.28  5056.1 2098.03
  5066.5 2099.68  5071.3 2101.35  5076.9 2103.29  5082.1 2107.30  5087.3 2118.50
  5097.7 2123.87  5116.3 2125.48  5128.8 2127.35  5136.3 2129.31  5138.6 2129.31
#Mann=4,-1,0
  4842.8    0.07       0  4990.7    0.07       0  4994.7    0.07       0
  5071.3    0.16       0
Bank Sta=4990.7,4994.7
Exp/Cntr=0.3,0.1

Type RM Length L Ch R = 1,832,74,74,74
BEGIN DESCRIPTION:
Elm 63 831.71
END DESCRIPTION:
XS GIS Cut Line= 3
      1521786.38      6770150.50      1521872.11      6770009.42
      1521915.53      6769898.71
#Sta/Elev= 30
  4831.7 2117.09  4839.6 2116.83  4846.3 2115.69  4855.0 2111.31  4860.9 2109.54
  4876.4 2112.34  4882.2 2108.83  4891.9 2107.83  4897.7 2098.30  4913.2 2093.62
  4934.5 2094.31  4955.8 2093.04  4992.7 2092.84  4994.7 2092.17  5007.1 2091.69
  5007.3 2091.19  5010.8 2091.19  5011.1 2091.69  5030.5 2093.27  5040.8 2095.06
  5046.2 2098.29  5052.0 2103.32  5062.8 2110.13  5070.6 2117.03  5076.0 2120.66
  5076.7 2120.67  5095.0 2121.49  5100.5 2122.64  5105.8 2121.92  5115.7 2122.67
#Mann=4,-1,0
  4831.7    0.07       0  5007.1    0.07       0  5011.1    0.07       0
  5076.7    0.16       0
Bank Sta=5007.1,5011.1
Exp/Cntr=0.3,0.1

Type RM Length L Ch R = 1,758,81,81,81
BEGIN DESCRIPTION:
Elm 63 757.56
END DESCRIPTION:
XS GIS Cut Line= 3
      1521843.91      6770165.65      1521924.20      6770064.76
      1521960.00      6769933.49
#Sta/Elev= 30
  4864.8 2115.43  4871.4 2115.33  4906.6 2113.42  4913.0 2113.49  4921.0 2112.61
  4926.1 2110.98  4927.4 2110.57  4935.5 2105.33  4941.8 2103.20  4949.9 2099.01
  4956.3 2098.55  4964.0 2093.94  4970.7 2092.11  5014.0 2090.29  5014.3 2089.79
  5017.8 2089.79  5018.0 2090.29  5021.5 2090.79  5031.8 2090.41  5042.2 2091.14
  5050.6 2095.82  5055.8 2096.02  5062.9 2107.15  5073.3 2111.48  5083.7 2111.83
  5095.5 2117.37  5109.5 2116.91  5114.8 2116.82  5124.9 2117.82  5129.8 2116.82
#Mann=5,-1,0
  4864.8    0.16       0  4926.1    0.07       0  5014.0    0.07       0
  5018.0    0.07       0  5109.5    0.16       0
Bank Sta=5014,5018
Exp/Cntr=0.3,0.1

Type RM Length L Ch R = 1,677,60,60,60
BEGIN DESCRIPTION:
Elm 63 676.89
END DESCRIPTION:
XS GIS Cut Line= 3
      1521979.54      6770190.58      1521996.90      6770085.37
      1522012.06      6769932.66
#Sta/Elev= 30
  4895.2 2107.42  4900.4 2107.26  4908.0 2108.03  4918.1 2108.52  4928.2 2108.51
  4948.5 2109.16  4951.0 2107.67  4956.5 2104.39  4961.6 2102.99  4968.8 2096.82
  4978.9 2092.75  4998.0 2087.92  5007.2 2087.76  5007.5 2087.26  5011.0 2087.26
  5011.2 2087.76  5019.3 2087.94  5028.8 2088.67  5033.8 2088.44  5039.4 2088.92
  5049.4 2089.06  5059.5 2088.92  5079.6 2090.61  5099.7 2100.19  5109.7 2106.68
  5116.5 2111.88  5119.8 2114.41  5129.6 2115.12  5139.9 2114.02  5155.3 2113.88
#Mann=5,-1,0
  4895.2    0.16       0  4951.0    0.07       0  5007.2    0.07       0
  5011.2    0.07       0  5116.5    0.16       0
Bank Sta=5007.2,5011.2
Exp/Cntr=0.3,0.1

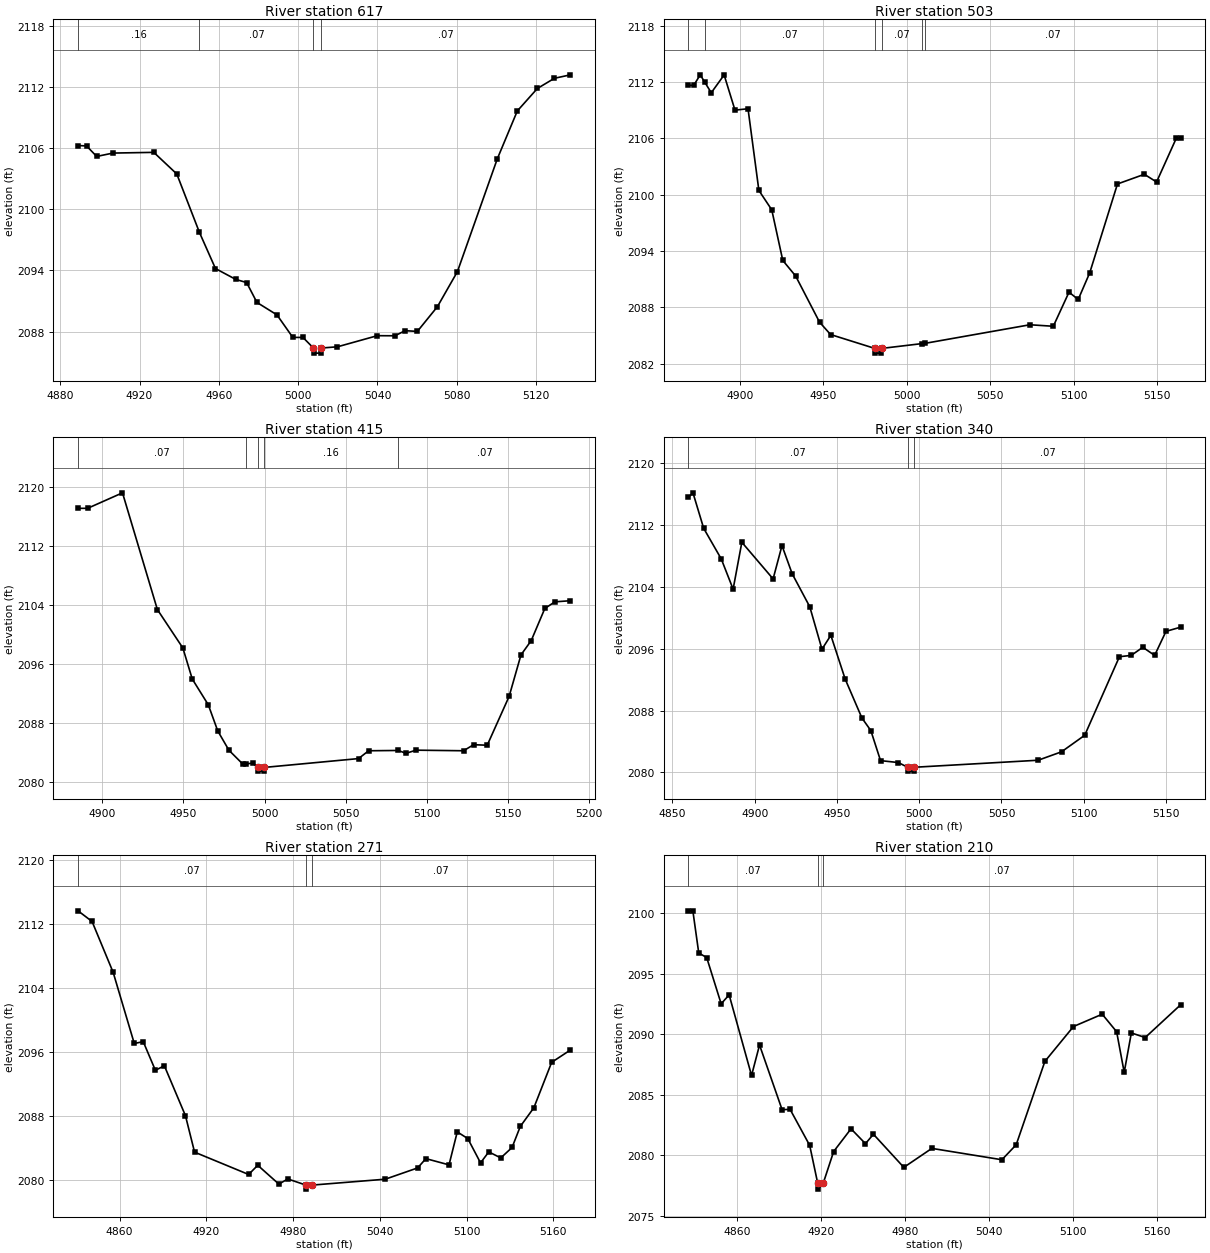
Type RM Length L Ch R = 1,617,114,114,114
BEGIN DESCRIPTION:
Elm 63 616.93
END DESCRIPTION:
XS GIS Cut Line= 3
      1522028.36      6770194.99      1522056.58      6770087.54
      1522039.43      6769951.41
#Sta/Elev= 30
  4889.0 2106.24  4893.3 2106.20  4898.4 2105.17  4906.6 2105.50  4927.2 2105.57
  4938.8 2103.45  4950.2 2097.73  4958.3 2094.18  4968.6 2093.11  4974.0 2092.81
  4979.2 2090.86  4989.3 2089.64  4997.3 2087.43  5002.4 2087.43  5007.7 2086.39
  5008.0 2085.89  5011.5 2085.89  5011.7 2086.39  5019.8 2086.51  5039.9 2087.60
  5048.8 2087.59  5053.9 2088.09  5060.1 2088.02  5070.2 2090.44  5080.3 2093.88
  5100.4 2104.93  5110.5 2109.63  5120.6 2111.83  5129.2 2112.83  5137.3 2113.17
#Mann=4,-1,0
  4889.0    0.16       0  4950.2    0.07       0  5007.7    0.07       0
  5011.7    0.07       0
Bank Sta=5007.7,5011.7
Exp/Cntr=0.3,0.1

Type RM Length L Ch R = 1,503,88,88,88
BEGIN DESCRIPTION:
Elm 63 503.281
END DESCRIPTION:
XS GIS Cut Line= 3
      1522254.97      6770187.97      1522170.20      6770088.49
      1522105.00      6769938.01
#Sta/Elev= 30
  4869.3 2111.63  4872.5 2111.63  4876.4 2112.75  4879.2 2111.94  4883.0 2110.84
  4890.7 2112.74  4897.2 2108.99  4905.0 2109.14  4911.5 2100.44  4919.2 2098.38
  4925.8 2092.99  4933.5 2091.33  4947.8 2086.42  4954.4 2085.10  4980.9 2083.62
  4981.2 2083.12  4984.7 2083.12  4984.9 2083.62  5009.4 2084.14  5011.2 2084.17
  5073.7 2086.14  5087.7 2085.98  5097.1 2089.61  5102.6 2088.83  5109.5 2091.67
  5126.1 2101.13  5142.2 2102.16  5149.5 2101.34  5161.3 2106.00  5164.0 2106.00
#Mann=6,-1,0
  4869.3    0.16       0  4879.2    0.07       0  4980.9    0.07       0
  4984.9    0.07       0  5009.4    0.16       0  5011.2    0.07       0
Bank Sta=4980.9,4984.9
Exp/Cntr=0.3,0.1

Type RM Length L Ch R = 1,415,75,75,75
BEGIN DESCRIPTION:
Elm 63 4950
END DESCRIPTION:
XS GIS Cut Line= 3
      1522302.89      6770148.30      1522244.80      6770049.05
      1522132.52      6769897.64
#Sta/Elev= 30
  4885.0 2117.05  4890.9 2117.05  4912.4 2119.15  4933.9 2103.33  4949.6 2098.13
  4955.4 2093.92  4965.3 2090.42  4971.1 2086.89  4978.0 2084.27  4986.8 2082.34
  4988.5 2082.40  4992.6 2082.54  4995.7 2081.94  4996.0 2081.44  4999.5 2081.44
  4999.7 2081.94  5057.9 2083.14  5064.1 2084.20  5082.4 2084.24  5087.1 2083.85
  5093.3 2084.28  5122.6 2084.20  5128.8 2085.02  5137.2 2084.95  5150.7 2091.57
  5158.0 2097.19  5164.3 2099.12  5172.7 2103.48  5178.9 2104.38  5188.5 2104.53
#Mann=5,-1,0
  4885.0    0.07       0  4988.5    0.16       0  4995.7    0.07       0
  4999.7    0.16       0  5082.4    0.07       0
Bank Sta=4995.7,4999.7
Exp/Cntr=0.3,0.1

Type RM Length L Ch R = 1,340,69,69,69
BEGIN DESCRIPTION:
Elm 63 4949
END DESCRIPTION:
XS GIS Cut Line= 3
      1522350.64      6770126.63      1522298.98      6769996.19
      1522184.62      6769885.72
#Sta/Elev= 30
  4859.7 2115.60  4862.5 2116.18  4869.0 2111.59  4879.7 2107.62  4886.9 2103.71
  4892.2 2109.78  4911.2 2105.04  4916.6 2109.35  4922.8 2105.70  4933.5 2101.43
  4940.9 2095.94  4946.3 2097.74  4955.0 2092.08  4965.2 2087.03  4970.6 2085.41
  4976.5 2081.52  4987.3 2081.27  4993.0 2080.66  4993.2 2080.16  4996.7 2080.16
  4997.0 2080.66  5072.3 2081.57  5086.5 2082.66  5100.6 2084.80  5121.7 2094.97
  5128.9 2095.14  5135.9 2096.19  5143.1 2095.14  5150.0 2098.25  5159.0 2098.80
#Mann=3,-1,0
  4859.7    0.07       0  4993.0    0.07       0  4997.0    0.07       0
Bank Sta=4993,4997
Exp/Cntr=0.3,0.1

Type RM Length L Ch R = 1,271,61,61,61
BEGIN DESCRIPTION:
Elm 63 4947
END DESCRIPTION:
XS GIS Cut Line= 3
      1522464.55      6770112.48      1522363.32      6769977.53
      1522212.85      6769894.41
#Sta/Elev= 30
  4831.3 2113.64  4841.0 2112.31  4855.6 2105.95  4870.2 2097.07  4876.4 2097.30
  4884.8 2093.72  4891.0 2094.29  4905.6 2088.05  4911.9 2083.50  4949.3 2080.71
  4955.6 2081.86  4970.2 2079.51  4976.4 2080.15  4989.0 2079.38  4989.3 2078.88
  4993.0 2079.38  5043.8 2080.12  5066.2 2081.53  5071.9 2082.69  5087.9 2081.91
  5093.6 2086.03  5100.9 2085.19  5109.7 2082.16  5115.4 2083.53  5123.7 2082.78
  5131.5 2084.08  5137.2 2086.71  5146.6 2089.05  5158.9 2094.72  5171.9 2096.26
#Mann=3,-1,0
  4831.3    0.07       0  4989.0    0.07       0  4993.0    0.07       0
Bank Sta=4989,4993
Exp/Cntr=0.3,0.1

Type RM Length L Ch R = 1,210,47,47,47
BEGIN DESCRIPTION:
Elm 63 4946
END DESCRIPTION:
XS GIS Cut Line= 3
      1522555.68      6770017.00      1522403.12      6769932.29
      1522230.22      6769894.41
#Sta/Elev= 30
  4825.5 2100.21  4828.7 2100.21  4832.9 2096.73  4838.6 2096.34  4848.9 2092.52
  4854.6 2093.26  4870.6 2086.59  4876.3 2089.11  4892.4 2083.76  4898.1 2083.79
  4912.1 2080.81  4917.8 2077.69  4918.1 2077.19  4921.8 2077.69  4929.2 2080.30
  4941.6 2082.18  4951.9 2080.95  4957.6 2081.73  4979.3 2078.99  4999.3 2080.56
  5049.3 2079.62  5059.5 2080.86  5080.0 2087.76  5100.4 2090.64  5120.9 2091.66
  5131.2 2090.21  5136.6 2086.85  5141.7 2090.11  5151.6 2089.73  5177.0 2092.45
#Mann=3,-1,0
  4825.5    0.07       0  4917.8    0.07       0  4921.8    0.07       0
Bank Sta=4917.8,4921.8
Exp/Cntr=0.3,0.1

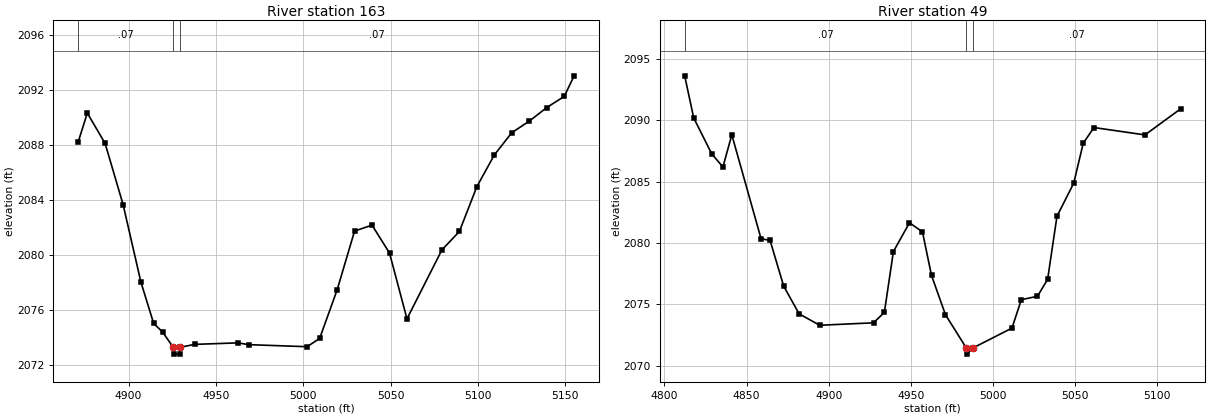
Type RM Length L Ch R = 1,163,114,114,114
BEGIN DESCRIPTION:
Elm 63 4945
END DESCRIPTION:
XS GIS Cut Line= 3
      1522530.05      6769913.01      1522404.43      6769884.53
      1522249.35      6769886.80
#Sta/Elev= 30
  4871.2 2088.21  4876.4 2090.31  4886.6 2088.10  4896.9 2083.64  4907.1 2078.00
  4914.4 2074.99  4919.5 2074.37  4925.6 2073.26  4925.9 2072.76  4929.4 2072.76
  4929.6 2073.26  4937.9 2073.47  4962.6 2073.58  4968.7 2073.45  5002.2 2073.30
  5009.4 2073.90  5019.4 2077.43  5029.4 2081.72  5039.4 2082.15  5049.4 2080.12
  5059.4 2075.33  5079.4 2080.35  5089.4 2081.69  5099.4 2084.95  5109.4 2087.26
  5119.4 2088.88  5129.4 2089.72  5139.4 2090.71  5149.4 2091.52  5155.1 2093.02
#Mann=3,-1,0
  4871.2    0.07       0  4925.6    0.07       0  4929.6    0.07       0
Bank Sta=4925.6,4929.6
Exp/Cntr=0.3,0.1

Type RM Length L Ch R = 1,49,0,0,0
BEGIN DESCRIPTION:
Elm 63 4944
END DESCRIPTION:
XS GIS Cut Line= 3
      1522530.04      6769863.02      1522358.65      6769786.49
      1522258.99      6769842.46
#Sta/Elev= 30
  4812.3 2093.61  4817.8 2090.18  4828.8 2087.25  4835.6 2086.19  4841.0 2088.81
  4858.8 2080.35  4864.3 2080.21  4872.6 2076.48  4882.0 2074.23  4894.5 2073.30
  4927.3 2073.50  4933.9 2074.35  4939.4 2079.30  4949.2 2081.65  4957.1 2080.90
  4962.6 2077.36  4971.1 2074.16  4983.8 2071.45  4984.1 2070.95  4987.8 2071.45
  5011.6 2073.07  5017.3 2075.38  5027.1 2075.66  5033.3 2077.03  5039.0 2082.17
  5049.2 2084.87  5055.0 2088.12  5061.5 2089.40  5092.6 2088.80  5114.3 2090.92
#Mann=3,-1,0
  4812.3    0.07       0  4983.8    0.07       0  4987.8    0.07       0
Bank Sta=4983.8,4987.8
Exp/Cntr=0.3,0.1

Chan Stop Cuts=-1