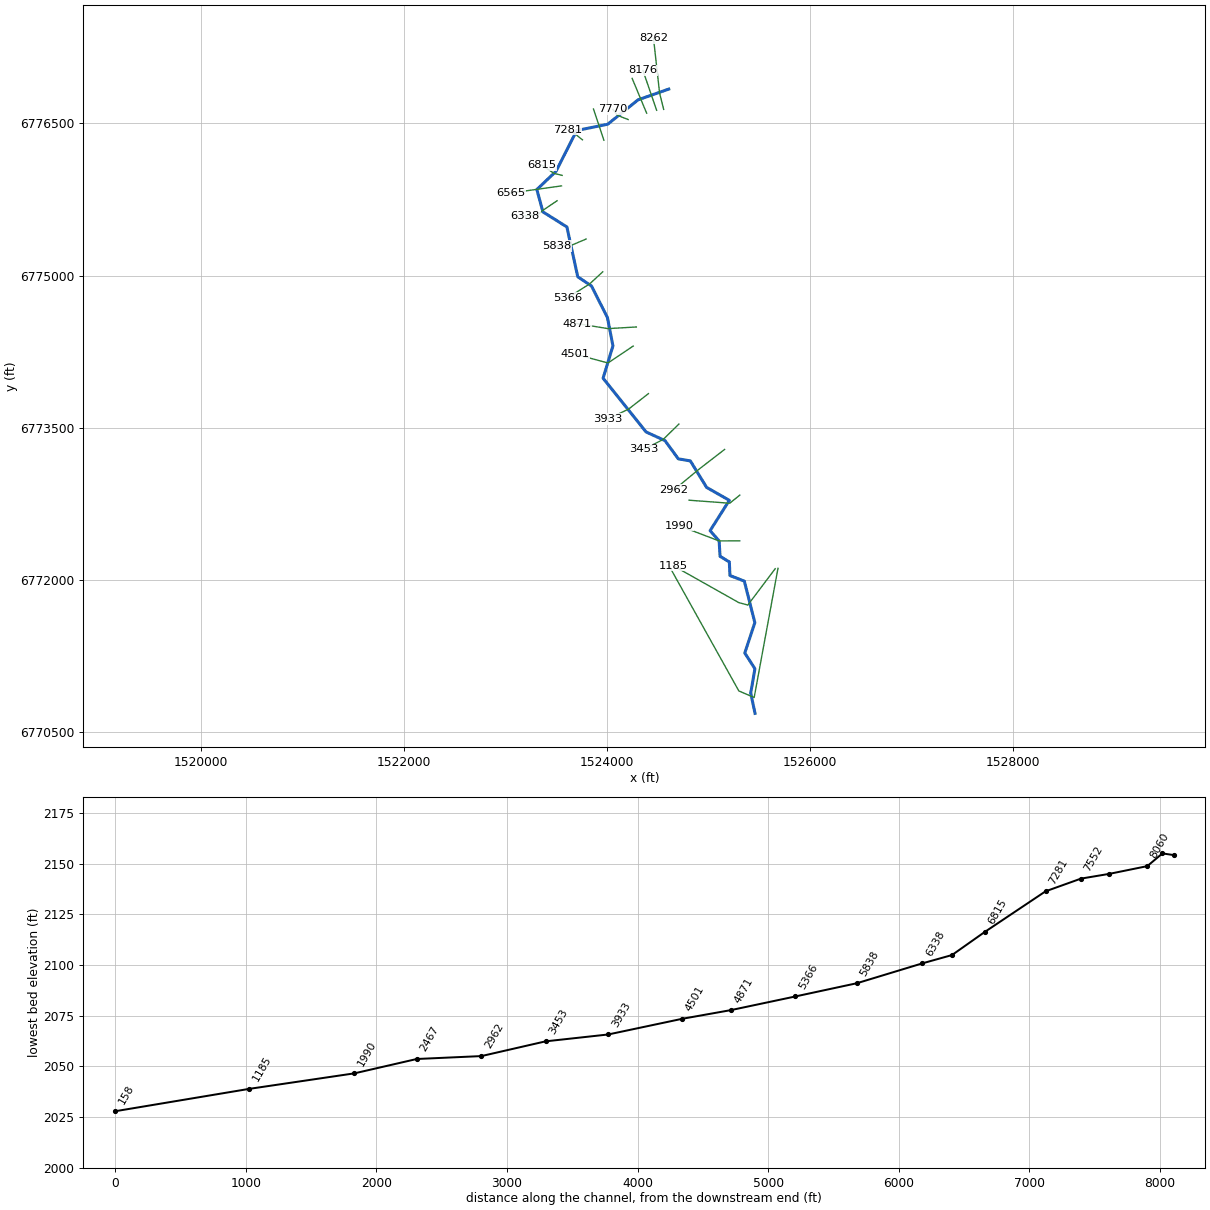
--- Elm 64.prj (project) ---

Proj Title=Elm 64 Base Level Engineering
Current Plan=p01
Default Exp/Contr=0.3,0.1
English Units
Geom File=g01
Flow File=f01
Plan File=p01
BEGIN DESCRIPTION:
Elm 64
END DESCRIPTION:

--- Elm 64.p01 (plan) ---

Plan Title=Multiple Run
Short Identifier=Multiple
Geom File=g01
Flow File=f01
Subcritical Flow
K Sum by GR= 0
Std Step Tol= 0.01
Critical Tol= 0.01
Num of Std Step Trials= 20
Max Error Tol= 0.3
Flow Tol Ratio= 0.001
Split Flow NTrial= 30
Split Flow Tol= 0.02
Split Flow Ratio= 0.02
Log Output Level= 0
Friction Slope Method= 1
Unsteady Friction Slope Method= 2
Unsteady Bridges Friction Slope Method= 1
Parabolic Critical Depth
Global Vel Dist=  1 , 1 , 1
Global Log Level= 0
CheckData=True
Encroach Param= -1, 0, 0, 0
BEGIN DESCRIPTION:
Multiple Run
END DESCRIPTION:

--- Elm 64.f01 (steady flow) ---

Flow Title=Multiple
Number of Profiles=7
Profile Names=10-year,25-year,50-year,1pct_min,100-year,1pct_plu,500-year
River Rch & RM= Elm 64,Reach-1,8262
     163     221     269     203     326     449     484
River Rch & RM= Elm 64,Reach-1,6815
     326     463     579     450     721     992    1130
Boundary for River Rch & Prof#=Elm 64,Reach-1,1
Up Type=0
Dn Type=3
Dn Slope=0.005
Boundary for River Rch & Prof#=Elm 64,Reach-1,2
Up Type=0
Dn Type=3
Dn Slope=0.005
Boundary for River Rch & Prof#=Elm 64,Reach-1,3
Up Type=0
Dn Type=3
Dn Slope=0.005
Boundary for River Rch & Prof#=Elm 64,Reach-1,4
Up Type=0
Dn Type=3
Dn Slope=0.005
Boundary for River Rch & Prof#=Elm 64,Reach-1,5
Up Type=0
Dn Type=3
Dn Slope=0.005
Boundary for River Rch & Prof#=Elm 64,Reach-1,6
Up Type=0
Dn Type=3
Dn Slope=0.005
Boundary for River Rch & Prof#=Elm 64,Reach-1,7
Up Type=0
Dn Type=3
Dn Slope=0.005

--- Elm 64.g01 (geometry) ---

Geom Title=Existing Conditions

River Reach=Elm 64,Reach-1
Reach XY= 30
      1524605.00      6776838.00      1524302.70      6776732.17
      1524003.50      6776491.62      1523698.48      6776430.32
      1523494.38      6776027.99      1523305.72      6775848.71
      1523365.48      6775628.20      1523601.63      6775479.85
      1523708.52      6774989.28      1523844.37      6774898.00
      1524001.25      6774586.45      1524055.28      6774308.18
      1523958.14      6773989.64      1524381.16      6773460.86
      1524568.57      6773374.53      1524698.81      6773195.86
      1524818.33      6773174.61      1524977.85      6772914.16
      1525201.99      6772786.57      1525012.30      6772487.92
      1525101.43      6772386.53      1525110.40      6772235.32
      1525201.89      6772179.67      1525207.95      6772045.99
      1525349.65      6771990.73      1525453.18      6771581.88
      1525354.15      6771282.95      1525453.95      6771127.56
      1525412.56      6770888.00      1525455.00      6770688.00

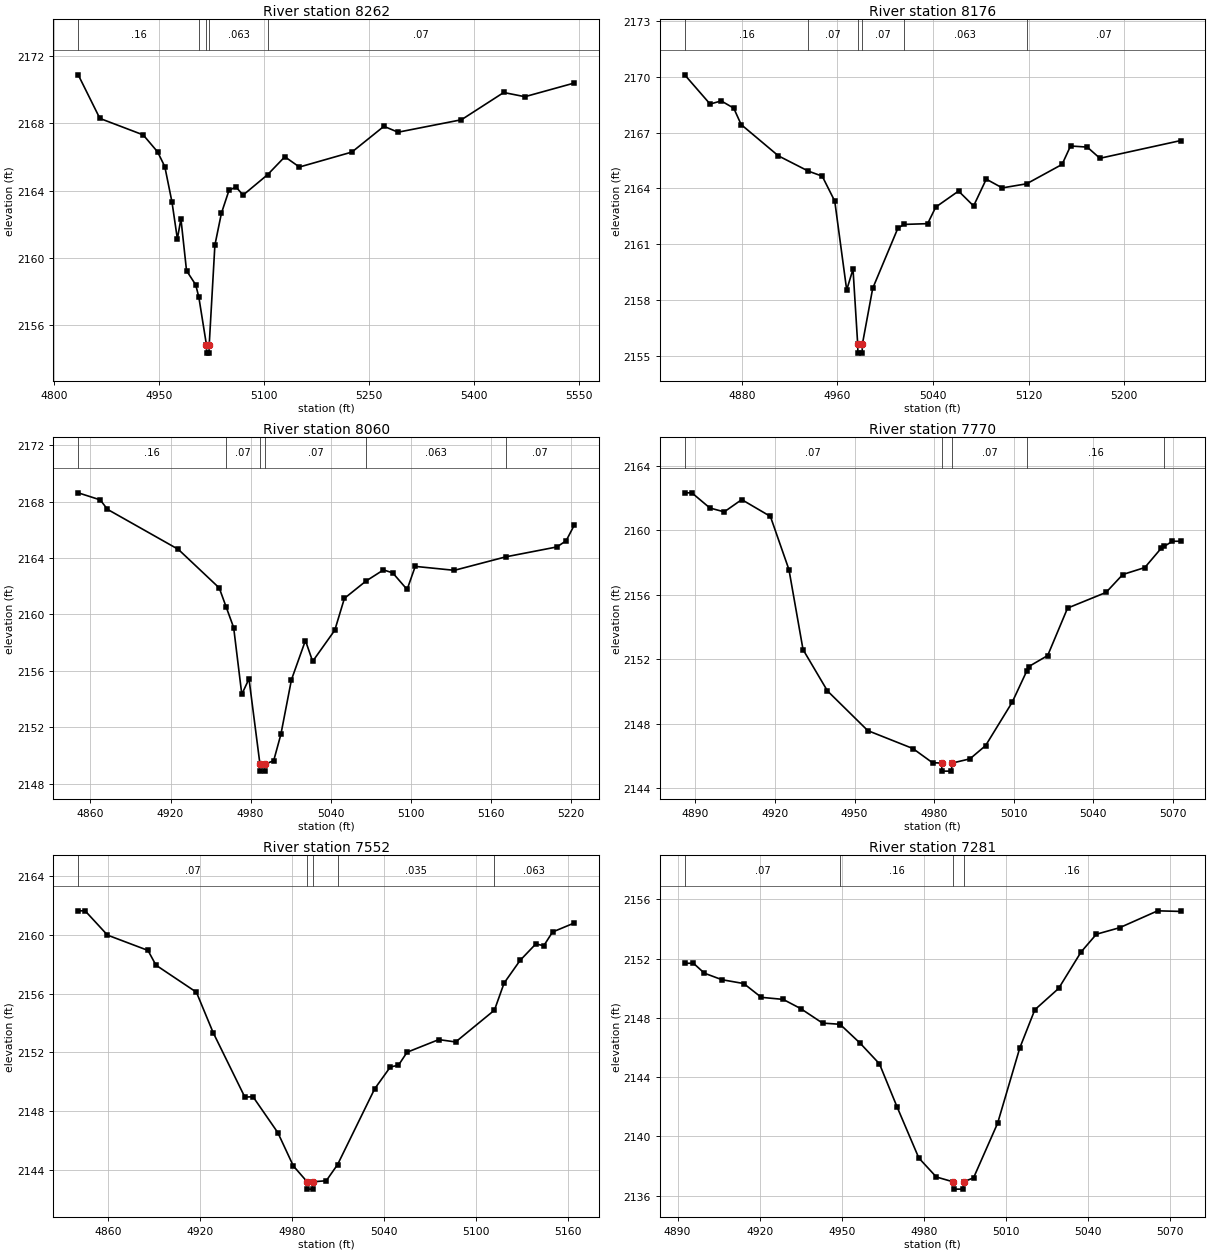
Type RM Length L Ch R = 1,8262,86,86,86
BEGIN DESCRIPTION:
375
END DESCRIPTION:
XS GIS Cut Line= 3
      1524555.00      6776637.98      1524514.75      6776798.61
      1524455.00      6777338.02
#Sta/Elev= 30
  4834.4 2170.88  4865.3 2168.29  4927.2 2167.31  4947.8 2166.30  4958.1 2165.42
  4968.4 2163.30  4976.0 2161.13  4981.1 2162.32  4989.1 2159.24  5002.2 2158.40
  5006.7 2157.66  5017.5 2154.84  5017.8 2154.34  5021.3 2154.34  5021.5 2154.84
  5029.6 2160.76  5038.9 2162.65  5049.7 2164.01  5059.7 2164.22  5069.8 2163.73
  5105.0 2164.95  5129.5 2166.01  5150.3 2165.40  5225.3 2166.29  5271.0 2167.82
  5291.2 2167.47  5381.7 2168.21  5442.1 2169.83  5472.3 2169.58  5542.7 2170.39
#Mann=5,-1,0
  4834.4    0.16       0  5006.7   0.063       0  5017.5    0.07       0
  5021.5   0.063       0  5105.0    0.07       0
Bank Sta=5017.5,5021.5
Exp/Cntr=0.3,0.1

Type RM Length L Ch R = 1,8176,116,116,116
BEGIN DESCRIPTION:
864
END DESCRIPTION:
XS GIS Cut Line= 2
      1524485.64      6776629.10      1524350.60      6777021.94
#Sta/Elev= 30
  4832.0 2170.10  4853.3 2168.53  4862.6 2168.70  4873.1 2168.31  4879.3 2167.43
  4910.5 2165.75  4935.6 2164.93  4947.2 2164.66  4957.7 2163.32  4967.7 2158.55
  4973.0 2159.67  4976.9 2155.66  4977.1 2155.16  4980.6 2155.16  4980.9 2155.66
  4989.5 2158.64  5010.6 2161.87  5015.8 2162.07  5035.5 2162.11  5042.3 2163.00
  5061.4 2163.86  5074.0 2163.06  5084.6 2164.50  5098.0 2164.03  5118.4 2164.25
  5148.1 2165.29  5155.2 2166.28  5169.2 2166.22  5179.8 2165.62  5247.4 2166.57
#Mann=6,-1,0
  4832.0    0.16       0  4935.6    0.07       0  4976.9    0.07       0
  4980.9    0.07       0  5015.8   0.063       0  5118.4    0.07       0
Bank Sta=4976.9,4980.9
Exp/Cntr=0.3,0.1

Type RM Length L Ch R = 1,8060,290,290,290
BEGIN DESCRIPTION:
863
END DESCRIPTION:
XS GIS Cut Line= 2
      1524387.43      6776600.45      1524244.47      6776943.56
#Sta/Elev= 30
  4850.8 2168.63  4867.3 2168.13  4872.7 2167.46  4925.8 2164.62  4956.5 2161.88
  4961.6 2160.55  4967.3 2159.07  4973.4 2154.33  4978.8 2155.43  4987.0 2149.38
  4987.2 2148.88  4990.7 2148.88  4991.0 2149.38  4997.3 2149.62  5002.7 2151.49
  5010.6 2155.36  5021.1 2158.15  5026.5 2156.67  5043.1 2158.88  5050.3 2161.14
  5066.5 2162.37  5079.6 2163.16  5086.5 2162.95  5097.3 2161.77  5103.4 2163.41
  5132.7 2163.13  5171.4 2164.09  5209.6 2164.79  5216.5 2165.23  5222.5 2166.32
#Mann=6,-1,0
  4850.8    0.16       0  4961.6    0.07       0  4987.0    0.07       0
  4991.0    0.07       0  5066.5   0.063       0  5171.4    0.07       0
Bank Sta=4987,4991
Exp/Cntr=0.3,0.1

Type RM Length L Ch R = 1,7770,218,218,218
BEGIN DESCRIPTION:
374
END DESCRIPTION:
XS GIS Cut Line= 3
      1524205.01      6776538.00      1524098.96      6776579.82
      1524055.01      6776637.98
#Sta/Elev= 30
  4886.0 2162.31  4888.7 2162.31  4895.5 2161.37  4900.9 2161.13  4907.5 2161.89
  4918.3 2160.85  4925.3 2157.55  4930.6 2152.60  4939.8 2150.04  4955.0 2147.58
  4972.0 2146.47  4979.4 2145.59  4982.8 2145.57  4983.0 2145.07  4986.5 2145.07
  4986.8 2145.57  4993.5 2145.83  4999.4 2146.65  5009.4 2149.33  5015.0 2151.30
  5015.7 2151.55  5022.8 2152.23  5030.3 2155.17  5044.8 2156.14  5051.1 2157.25
  5059.4 2157.68  5065.6 2158.88  5066.7 2158.99  5069.8 2159.31  5072.9 2159.31
#Mann=5,-1,0
  4886.0    0.07       0  4982.8    0.07       0  4986.8    0.07       0
  5015.0    0.16       0  5066.7   0.035       0
Bank Sta=4982.8,4986.8
Exp/Cntr=0.3,0.1

Type RM Length L Ch R = 1,7552,271,271,271
BEGIN DESCRIPTION:
862
END DESCRIPTION:
XS GIS Cut Line= 2
      1523965.92      6776334.48      1523863.62      6776641.38
#Sta/Elev= 30
  4840.5 2161.62  4845.0 2161.62  4859.6 2159.97  4886.0 2158.93  4891.2 2157.93
  4917.6 2156.09  4928.5 2153.35  4949.2 2148.96  4954.5 2148.99  4970.7 2146.55
  4980.8 2144.29  4989.8 2143.21  4990.0 2142.71  4993.5 2142.71  4993.8 2143.21
  5002.3 2143.28  5009.7 2144.38  5033.9 2149.53  5044.1 2151.01  5049.4 2151.13
  5055.0 2152.01  5075.7 2152.87  5086.7 2152.71  5112.0 2154.87  5118.3 2156.71
  5128.8 2158.26  5139.0 2159.37  5144.2 2159.25  5149.9 2160.18  5164.0 2160.79
#Mann=5,-1,0
  4840.5    0.07       0  4989.8    0.07       0  4993.8    0.07       0
  5009.7   0.035       0  5112.0   0.063       0
Bank Sta=4989.8,4993.8
Exp/Cntr=0.3,0.1

Type RM Length L Ch R = 1,7281,466,466,466
BEGIN DESCRIPTION:
373
END DESCRIPTION:
XS GIS Cut Line= 3
      1523755.02      6776337.99      1523671.27      6776405.22
      1523605.03      6776437.99
#Sta/Elev= 30
  4892.6 2151.69  4895.8 2151.69  4899.8 2151.02  4906.2 2150.58  4914.2 2150.32
  4920.6 2149.39  4928.6 2149.25  4935.0 2148.63  4943.0 2147.65  4949.4 2147.57
  4949.5 2147.55  4956.7 2146.30  4963.8 2144.90  4970.2 2142.01  4978.2 2138.54
  4984.6 2137.26  4990.6 2136.94  4990.9 2136.44  4994.4 2136.44  4994.6 2136.94
  4998.2 2137.20  5007.0 2140.89  5015.1 2145.97  5020.6 2148.55  5029.3 2149.99
  5037.5 2152.45  5043.1 2153.65  5051.6 2154.09  5065.5 2155.23  5073.9 2155.19
#Mann=4,-1,0
  4892.6    0.07       0  4949.5    0.16       0  4990.6    0.07       0
  4994.6    0.16       0
Bank Sta=4990.6,4994.6
Exp/Cntr=0.3,0.1

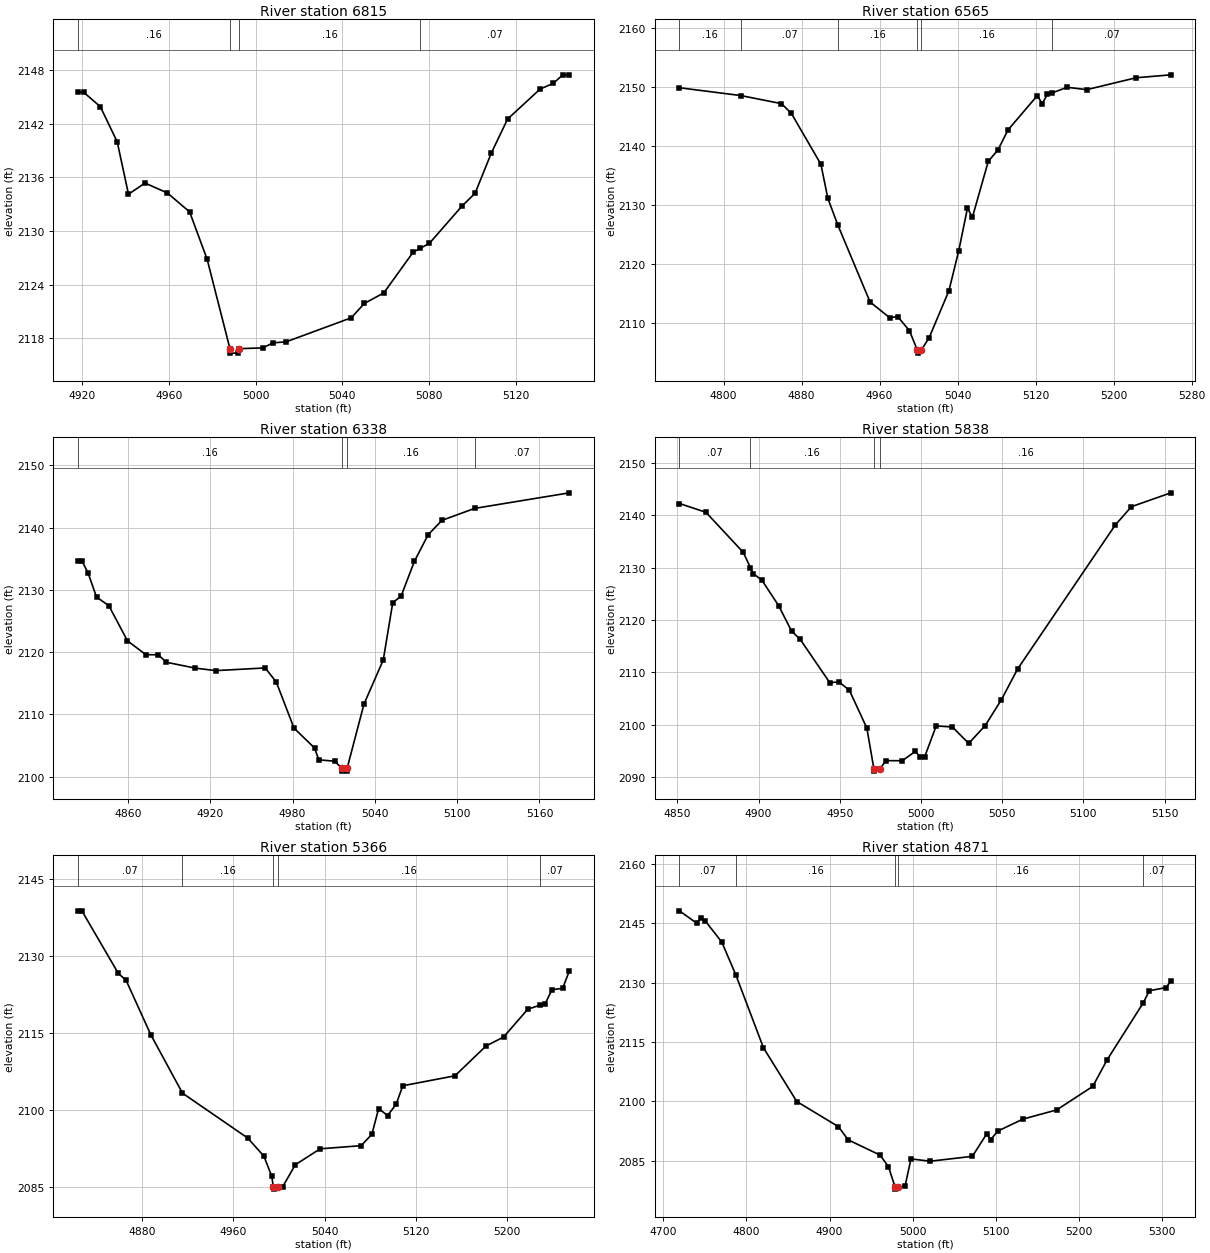
Type RM Length L Ch R = 1,6815,250,250,250
BEGIN DESCRIPTION:
372
END DESCRIPTION:
XS GIS Cut Line= 3
      1523554.99      6775988.00      1523475.48      6776007.63
      1523355.02      6776087.99
#Sta/Elev= 30
  4918.1 2145.49  4920.7 2145.49  4928.4 2143.89  4936.2 2139.95  4941.4 2134.10
  4949.0 2135.35  4959.3 2134.25  4969.6 2132.13  4977.7 2126.82  4988.2 2116.85
  4988.4 2116.35  4991.9 2116.35  4992.2 2116.85  5003.3 2116.93  5008.1 2117.50
  5014.1 2117.61  5044.2 2120.30  5050.2 2121.90  5059.2 2123.08  5072.7 2127.62
  5076.1 2128.07  5080.2 2128.61  5095.3 2132.79  5101.3 2134.21  5108.8 2138.71
  5116.3 2142.50  5131.3 2145.85  5137.3 2146.48  5141.8 2147.44  5144.8 2147.44
#Mann=4,-1,0
  4918.1    0.16       0  4988.2    0.07       0  4992.2    0.16       0
  5076.1    0.07       0
Bank Sta=4988.2,4992.2
Exp/Cntr=0.3,0.1

Type RM Length L Ch R = 1,6565,227,227,227
BEGIN DESCRIPTION:
860
END DESCRIPTION:
XS GIS Cut Line= 2
      1523548.56      6775884.29      1523049.58      6775814.77
#Sta/Elev= 30
  4754.8 2149.91  4817.7 2148.59  4859.4 2147.22  4869.5 2145.58  4899.8 2136.96
  4906.9 2131.21  4917.2 2126.66  4950.2 2113.64  4970.4 2110.97  4978.5 2111.18
  4990.6 2108.78  4998.7 2105.48  4999.0 2104.98  5002.7 2105.48  5010.8 2107.60
  5031.0 2115.51  5041.1 2122.28  5050.1 2129.55  5055.1 2127.96  5071.4 2137.44
  5081.5 2139.43  5091.6 2142.76  5121.7 2148.58  5126.7 2147.20  5132.0 2148.80
  5136.6 2149.02  5152.2 2149.99  5172.4 2149.59  5222.8 2151.60  5258.6 2152.10
#Mann=6,-1,0
  4754.8    0.16       0  4817.7    0.07       0  4917.2    0.16       0
  4998.7    0.07       0  5002.7    0.16       0  5136.6    0.07       0
Bank Sta=4998.7,5002.7
Exp/Cntr=0.3,0.1

Type RM Length L Ch R = 1,6338,500,500,500
BEGIN DESCRIPTION:
371
END DESCRIPTION:
XS GIS Cut Line= 4
      1523504.99      6775737.99      1523358.54      6775639.47
      1523319.33      6775601.78      1523192.50      6775589.65
#Sta/Elev= 30
  4823.5 2134.59  4826.5 2134.59  4831.0 2132.62  4837.0 2128.83  4846.0 2127.45
  4859.6 2121.80  4873.0 2119.58  4882.0 2119.56  4888.0 2118.36  4909.0 2117.42
  4924.0 2117.02  4960.0 2117.45  4968.1 2115.18  4981.0 2107.79  4996.0 2104.59
  4999.1 2102.69  5010.6 2102.48  5015.8 2101.38  5016.1 2100.88  5019.6 2100.88
  5019.8 2101.38  5032.0 2111.63  5046.1 2118.74  5053.0 2127.92  5059.1 2128.99
  5068.8 2134.57  5078.8 2138.84  5088.9 2141.15  5112.7 2143.07  5181.8 2145.57
#Mann=4,-1,0
  4823.5    0.16       0  5015.8    0.07       0  5019.8    0.16       0
  5112.7    0.07       0
Bank Sta=5015.8,5019.8
Exp/Cntr=0.3,0.1

Type RM Length L Ch R = 1,5838,472,472,472
BEGIN DESCRIPTION:
370
END DESCRIPTION:
XS GIS Cut Line= 3
      1523791.20      6775361.00      1523654.38      6775302.75
      1523500.79      6775292.95
#Sta/Elev= 30
  4851.3 2142.23  4867.6 2140.55  4890.6 2132.89  4895.0 2129.98  4896.7 2128.85
  4902.1 2127.56  4912.4 2122.70  4920.3 2117.87  4925.7 2116.25  4943.9 2107.98
  4949.4 2108.15  4955.9 2106.56  4966.7 2099.31  4971.0 2091.59  4971.2 2091.09
  4975.0 2091.59  4978.4 2093.09  4988.5 2093.08  4996.6 2094.87  4999.7 2093.74
  5002.2 2093.74  5009.4 2099.73  5019.4 2099.52  5029.4 2096.39  5039.5 2099.76
  5049.5 2104.70  5059.5 2110.59  5119.6 2138.09  5129.6 2141.62  5153.9 2144.27
#Mann=4,-1,0
  4851.3    0.07       0  4895.0    0.16       0  4971.0    0.07       0
  4975.0    0.16       0
Bank Sta=4971,4975
Exp/Cntr=0.3,0.1

Type RM Length L Ch R = 1,5366,495,495,495
BEGIN DESCRIPTION:
369
END DESCRIPTION:
XS GIS Cut Line= 3
      1523954.98      6775037.98      1523825.47      6774918.37
      1523610.06      6774783.01
#Sta/Elev= 30
  4823.7 2138.71  4827.1 2138.71  4859.1 2126.52  4865.9 2125.17  4887.5 2114.60
  4915.3 2103.22  4972.5 2094.48  4986.7 2090.94  4993.5 2087.05  4994.9 2085.04
  4995.2 2084.54  4998.9 2085.04  5003.2 2085.04  5014.2 2089.29  5036.0 2092.39
  5071.9 2093.00  5081.3 2095.22  5087.2 2100.22  5095.0 2098.87  5102.5 2101.03
  5108.4 2104.66  5154.1 2106.60  5181.4 2112.41  5196.7 2114.14  5217.9 2119.55
  5228.3 2120.33  5233.2 2120.63  5239.1 2123.36  5248.5 2123.62  5254.4 2127.04
#Mann=5,-1,0
  4823.7    0.07       0  4915.3    0.16       0  4994.9    0.07       0
  4998.9    0.16       0  5228.3    0.07       0
Bank Sta=4994.9,4998.9
Exp/Cntr=0.3,0.1

Type RM Length L Ch R = 1,4871,370,370,370
BEGIN DESCRIPTION:
368
END DESCRIPTION:
XS GIS Cut Line= 3
      1524285.83      6774494.49      1524005.80      6774478.32
      1523699.49      6774528.53
#Sta/Elev= 30
  4719.5 2148.15  4740.3 2145.01  4745.3 2146.41  4750.4 2145.64  4770.4 2140.25
  4787.3 2131.95  4820.5 2113.52  4860.6 2099.93  4910.7 2093.57  4922.3 2090.25
  4960.7 2086.39  4970.8 2083.46  4978.8 2078.28  4979.0 2077.78  4982.8 2078.28
  4990.8 2078.56  4997.9 2085.42  5021.1 2084.84  5071.7 2086.07  5088.8 2091.70
  5093.9 2090.30  5102.1 2092.44  5132.5 2095.48  5173.1 2097.81  5216.5 2103.76
  5233.9 2110.53  5277.2 2124.87  5284.5 2127.94  5304.8 2128.75  5310.4 2130.44
#Mann=5,-1,0
  4719.5    0.07       0  4787.3    0.16       0  4978.8    0.07       0
  4982.8    0.16       0  5277.2    0.07       0
Bank Sta=4978.8,4982.8
Exp/Cntr=0.3,0.1

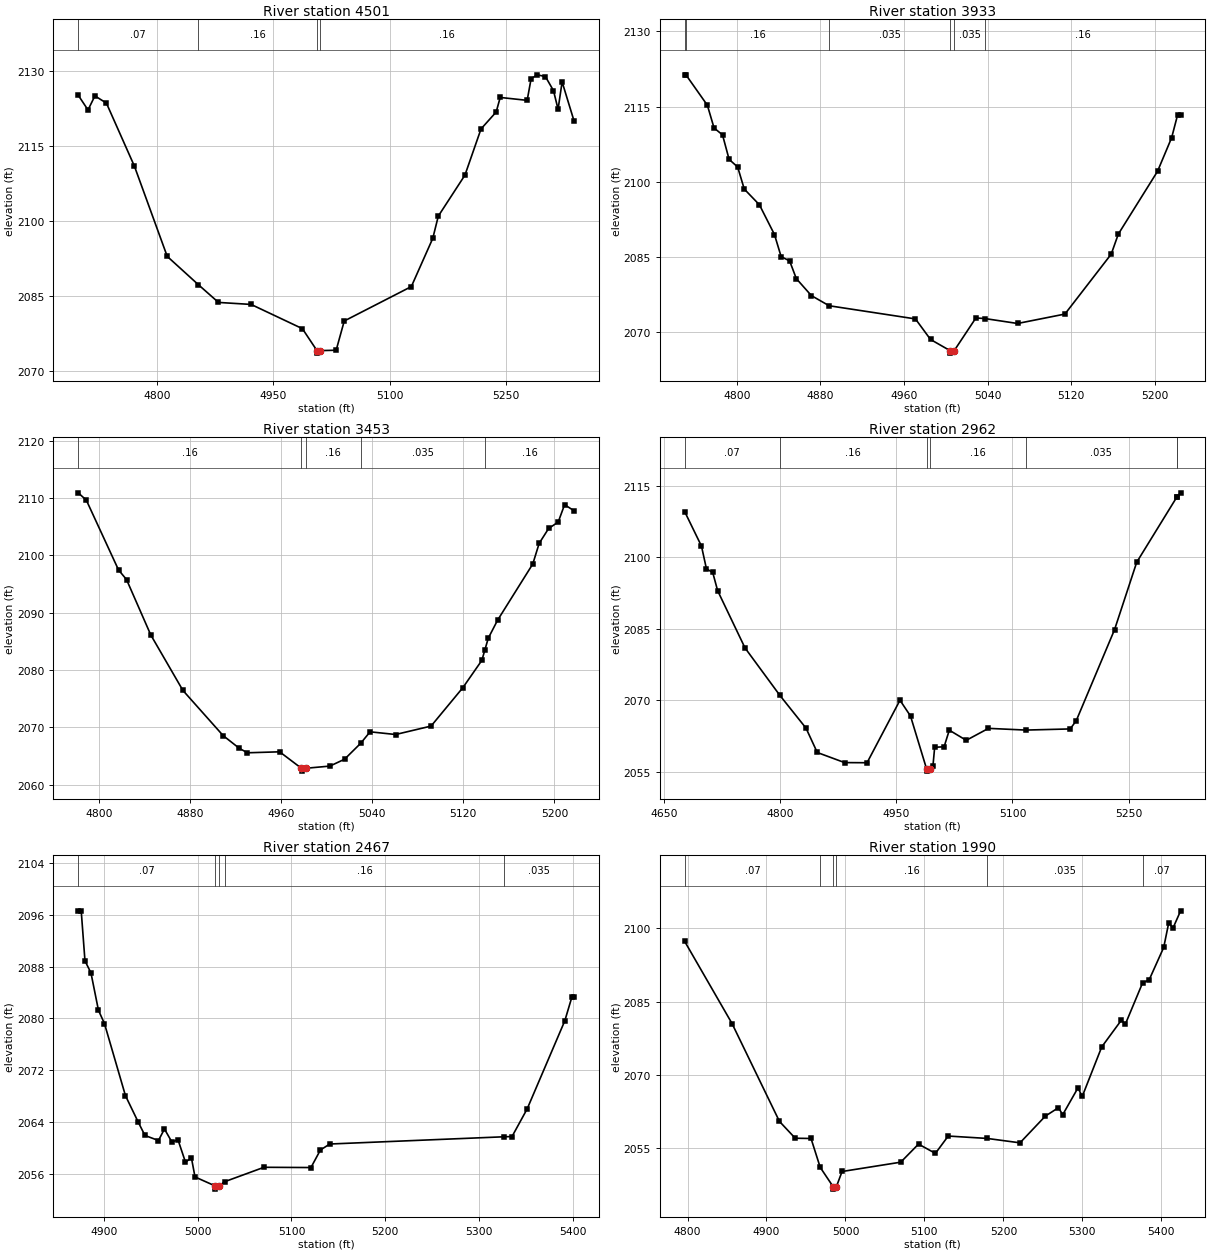
Type RM Length L Ch R = 1,4501,568,568,568
BEGIN DESCRIPTION:
367
END DESCRIPTION:
XS GIS Cut Line= 3
      1524255.11      6774306.86      1524006.08      6774139.70
      1523679.28      6774228.21
#Sta/Elev= 30
  4698.8 2125.07  4711.4 2122.12  4720.3 2124.93  4735.1 2123.49  4771.2 2110.87
  4813.4 2092.86  4853.4 2087.22  4879.4 2083.66  4921.4 2083.26  4987.4 2078.42
  5006.2 2074.03  5006.4 2073.53  5010.2 2074.03  5030.9 2074.11  5041.3 2079.95
  5127.7 2086.83  5155.3 2096.47  5162.4 2100.91  5196.7 2109.10  5217.4 2118.33
  5236.9 2121.71  5242.1 2124.62  5276.8 2124.04  5281.9 2128.38  5289.9 2129.14
  5300.3 2128.79  5310.7 2125.98  5316.6 2122.26  5321.8 2127.73  5337.3 2119.85
#Mann=4,-1,0
  4698.8    0.07       0  4853.4    0.16       0  5006.2    0.07       0
  5010.2    0.16       0
Bank Sta=5006.2,5010.2
Exp/Cntr=0.3,0.1

Type RM Length L Ch R = 1,3933,480,480,480
BEGIN DESCRIPTION:
366
END DESCRIPTION:
XS GIS Cut Line= 3
      1524405.00      6773838.00      1524207.93      6773684.49
      1524005.01      6773588.00
#Sta/Elev= 30
  4750.2 2121.34  4751.4 2121.34  4771.9 2115.27  4778.3 2110.73  4786.4 2109.35
  4792.7 2104.46  4800.9 2102.93  4807.2 2098.53  4821.7 2095.39  4836.1 2089.45
  4842.5 2085.03  4850.6 2084.19  4857.0 2080.65  4871.4 2077.26  4888.4 2075.23
  4971.0 2072.60  4985.4 2068.50  5004.1 2066.27  5004.4 2065.77  5008.1 2066.27
  5028.8 2072.79  5037.2 2072.68  5068.7 2071.69  5114.0 2073.57  5158.3 2085.54
  5165.1 2089.54  5202.6 2102.07  5216.1 2108.78  5221.9 2113.41  5224.7 2113.41
#Mann=6,-1,0
  4750.2    0.07       0  4751.4    0.16       0  4888.4   0.035       0
  5004.1   0.035       0  5008.1   0.035       0  5037.2    0.16       0
Bank Sta=5004.1,5008.1
Exp/Cntr=0.3,0.1

Type RM Length L Ch R = 1,3453,491,491,491
BEGIN DESCRIPTION:
365
END DESCRIPTION:
XS GIS Cut Line= 3
      1524705.00      6773538.00      1524549.15      6773385.58
      1524354.99      6773287.99
#Sta/Elev= 30
  4782.0 2110.93  4789.1 2109.66  4817.4 2097.47  4824.4 2095.80  4845.7 2086.13
  4873.9 2076.45  4909.2 2068.57  4923.4 2066.35  4930.5 2065.57  4958.8 2065.74
  4977.9 2062.87  4978.2 2062.37  4981.9 2062.87  5002.9 2063.25  5015.8 2064.45
  5029.9 2067.22  5038.2 2069.23  5060.6 2068.76  5091.7 2070.23  5119.6 2076.93
  5136.3 2081.70  5138.8 2083.42  5141.9 2085.56  5150.1 2088.71  5181.0 2098.52
  5186.6 2102.12  5194.9 2104.71  5203.3 2105.83  5208.9 2108.86  5217.3 2107.79
#Mann=5,-1,0
  4782.0    0.16       0  4977.9    0.07       0  4981.9    0.16       0
  5029.9   0.035       0  5138.8    0.16       0
Bank Sta=4977.9,4981.9
Exp/Cntr=0.3,0.1

Type RM Length L Ch R = 1,2962,495,495,495
BEGIN DESCRIPTION:
364
END DESCRIPTION:
XS GIS Cut Line= 3
      1525154.99      6773288.00      1524899.17      6773090.31
      1524655.00      6772888.00
#Sta/Elev= 30
  4676.7 2109.53  4698.4 2102.29  4704.8 2097.52  4712.9 2096.77  4719.3 2092.93
  4754.6 2080.94  4799.7 2070.97  4833.4 2064.11  4847.9 2059.01  4883.2 2056.89
  4912.2 2056.86  4954.7 2069.97  4968.3 2066.66  4989.0 2055.60  4989.2 2055.10
  4993.0 2055.60  4997.3 2056.20  4999.5 2060.10  5011.7 2060.21  5018.4 2063.69
  5040.3 2061.56  5069.0 2064.07  5117.2 2063.71  5174.5 2063.95  5182.3 2065.67
  5231.8 2084.78  5260.4 2098.91  5311.9 2112.50  5312.2 2112.65  5317.1 2113.47
#Mann=7,-1,0
  4676.7    0.07       0  4799.7    0.16       0  4989.0    0.07       0
  4993.0    0.16       0  5117.2   0.035       0  5311.9    0.16       0
  5312.2    0.07       0
Bank Sta=4989,4993
Exp/Cntr=0.3,0.1

Type RM Length L Ch R = 1,2467,477,477,477
BEGIN DESCRIPTION:
363
END DESCRIPTION:
XS GIS Cut Line= 3
      1525304.98      6772837.98      1525205.50      6772758.23
      1524805.01      6772788.00
#Sta/Elev= 30
  4872.5 2096.60  4875.7 2096.60  4879.7 2088.89  4886.1 2087.02  4894.1 2081.25
  4900.5 2079.21  4922.9 2068.08  4936.6 2063.98  4943.7 2061.94  4958.1 2061.16
  4964.5 2062.94  4972.5 2060.91  4978.9 2061.30  4986.9 2057.83  4993.3 2058.47
  4997.1 2055.54  5018.5 2054.16  5018.8 2053.66  5022.6 2054.16  5029.0 2054.82
  5070.7 2057.03  5120.8 2056.99  5130.9 2059.70  5140.9 2060.62  5327.2 2061.74
  5335.3 2061.77  5351.5 2066.05  5391.6 2079.62  5399.1 2083.26  5401.6 2083.26
#Mann=5,-1,0
  4872.5    0.07       0  5018.5    0.07       0  5022.6    0.07       0
  5029.0    0.16       0  5327.2   0.035       0
Bank Sta=5018.5,5022.6
Exp/Cntr=0.3,0.1

Type RM Length L Ch R = 1,1990,805,805,805
BEGIN DESCRIPTION:
362
END DESCRIPTION:
XS GIS Cut Line= 3
      1525305.03      6772388.00      1525101.43      6772386.53
      1524704.98      6772538.01
#Sta/Elev= 30
  4796.4 2097.31  4856.4 2080.48  4916.4 2060.45  4936.4 2057.00  4956.4 2056.95
  4968.0 2051.04  4984.4 2047.08  4984.6 2046.58  4988.5 2047.08  4995.7 2050.19
  5070.0 2052.10  5092.5 2055.80  5113.9 2053.90  5130.1 2057.45  5179.5 2056.96
  5221.0 2056.06  5253.1 2061.53  5269.7 2063.26  5275.1 2061.82  5294.4 2067.31
  5299.8 2065.55  5324.5 2075.70  5349.2 2081.14  5354.6 2080.43  5376.2 2088.80
  5384.6 2089.45  5403.0 2096.08  5409.4 2101.16  5414.7 2100.02  5424.4 2103.57
#Mann=6,-1,0
  4796.4    0.07       0  4968.0    0.16       0  4984.4    0.07       0
  4988.5    0.16       0  5179.5   0.035       0  5376.2    0.07       0
Bank Sta=4984.4,4988.5
Exp/Cntr=0.3,0.1

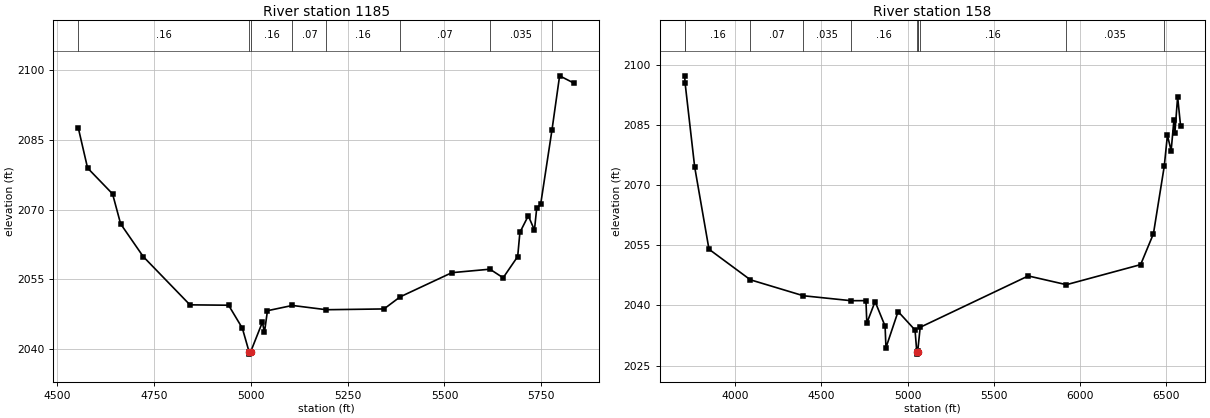
Type RM Length L Ch R = 1,1185,1027,1027,1027
BEGIN DESCRIPTION:
790
END DESCRIPTION:
XS GIS Cut Line= 4
      1525653.82      6772113.35      1525384.29      6771755.12
      1525295.60      6771779.00      1524649.64      6772142.77
#Sta/Elev= 30
  4553.6 2087.65  4577.8 2078.95  4642.4 2073.38  4663.2 2066.94  4721.5 2059.91
  4842.3 2049.52  4942.2 2049.44  4977.7 2044.50  4995.1 2039.42  4995.4 2038.92
  4999.2 2039.42  5029.6 2045.80  5034.8 2043.58  5042.6 2048.26  5107.0 2049.39
  5194.9 2048.47  5343.8 2048.64  5385.3 2051.23  5519.1 2056.44  5617.5 2057.19
  5651.6 2055.34  5689.2 2059.91  5694.9 2065.10  5716.6 2068.68  5732.5 2065.60
  5738.3 2070.27  5748.5 2071.12  5777.8 2087.13  5797.5 2098.78  5835.1 2097.19
#Mann=8,-1,0
  4553.6    0.16       0  4995.1    0.07       0  4999.2    0.16       0
  5107.0    0.07       0  5194.9    0.16       0  5385.3    0.07       0
  5617.5   0.035       0  5777.8    0.07       0
Bank Sta=4995.1,4999.2
Exp/Cntr=0.3,0.1

Type RM Length L Ch R = 1,158,0,0,0
BEGIN DESCRIPTION:
361
END DESCRIPTION:
XS GIS Cut Line= 4
      1525681.09      6772116.76      1525446.55      6770844.19
      1525295.60      6770909.08      1524603.09      6772150.82
#Sta/Elev= 30
  3706.0 2097.24  3708.6 2095.37  3763.9 2074.57  3847.1 2054.02  4087.4 2046.40
  4395.4 2042.42  4672.5 2041.19  4758.7 2041.20  4763.8 2035.59  4811.7 2040.97
  4869.8 2034.86  4874.9 2029.47  4945.3 2038.49  5043.7 2033.88  5054.1 2028.37
  5054.3 2027.87  5058.2 2028.37  5059.6 2028.71  5073.7 2034.56  5701.2 2047.36
  5922.8 2045.18  6353.9 2050.18  6428.2 2057.88  6491.0 2074.68  6509.4 2082.40
  6531.1 2078.61  6547.1 2086.16  6552.8 2083.04  6568.8 2092.00  6586.1 2084.64
#Mann=11,-1,0
  3706.0    0.07       0  3708.6    0.16       0  4087.4    0.07       0
  4395.4   0.035       0  4672.5    0.16       0  5054.1    0.07       0
  5058.2    0.16       0  5059.6    0.12       0  5073.7    0.16       0
  5922.8   0.035       0  6491.0    0.07       0
Bank Sta=5054.1,5058.2
Exp/Cntr=0.3,0.1

Chan Stop Cuts=-1