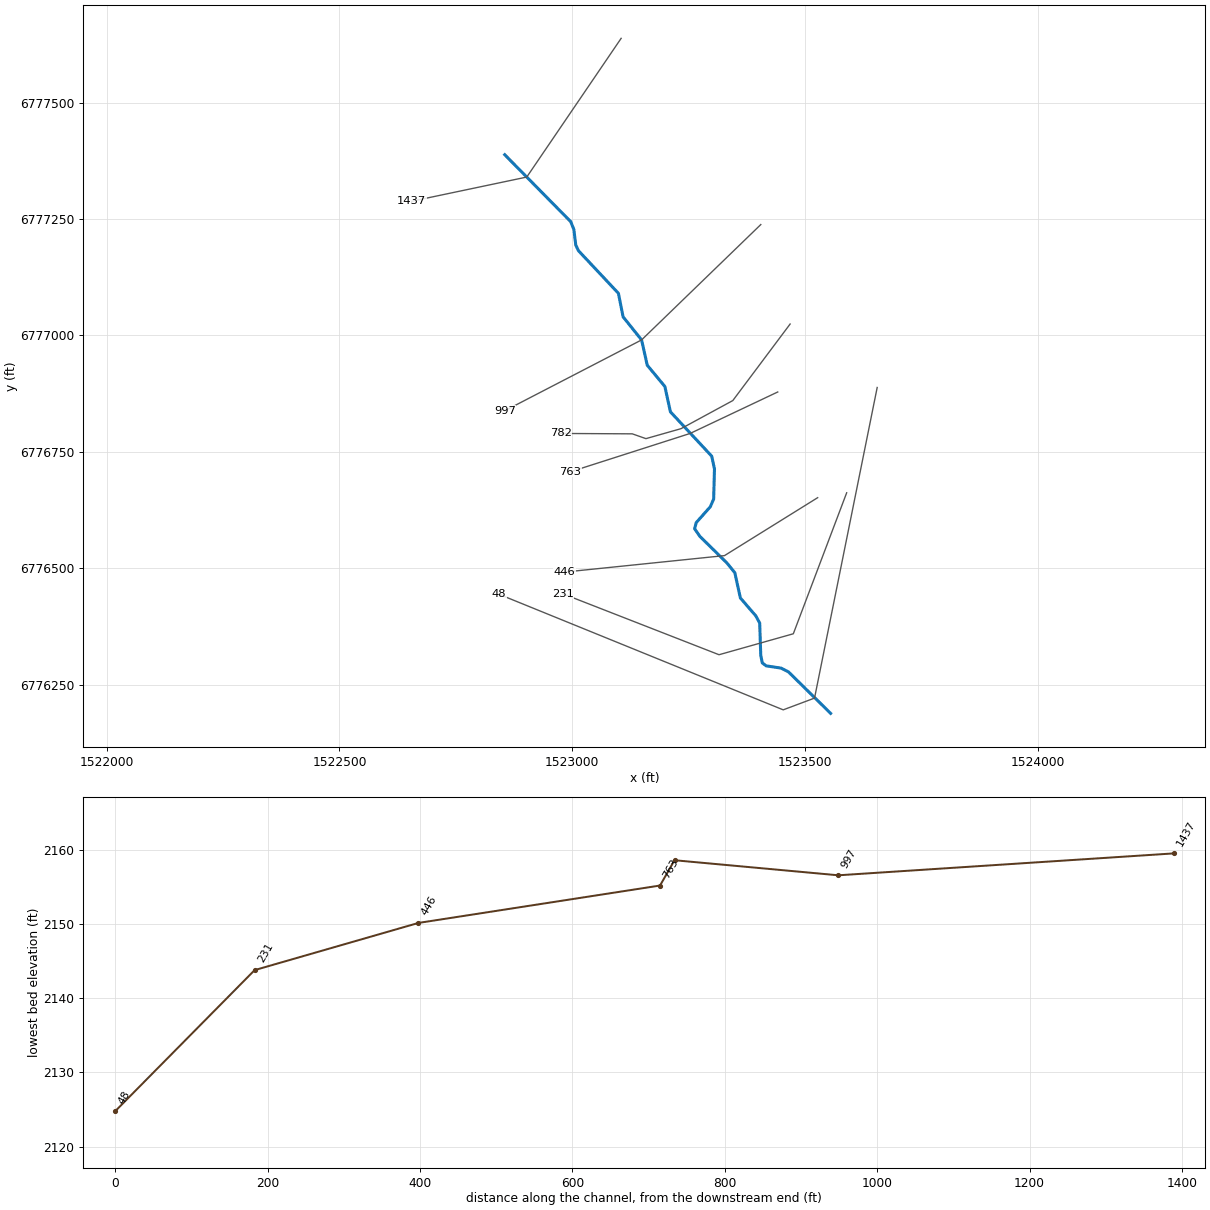
--- Elm 65.prj (project) ---

Proj Title=Elm 65 Base Level Engineering
Current Plan=p01
Default Exp/Contr=0.3,0.1
English Units
Geom File=g01
Flow File=f01
Plan File=p01
BEGIN DESCRIPTION:
Elm 65
END DESCRIPTION:

--- Elm 65.p01 (plan) ---

Plan Title=Multiple Run
Short Identifier=Multiple
Geom File=g01
Flow File=f01
Subcritical Flow
K Sum by GR= 0
Std Step Tol= 0.01
Critical Tol= 0.01
Num of Std Step Trials= 20
Max Error Tol= 0.3
Flow Tol Ratio= 0.001
Split Flow NTrial= 30
Split Flow Tol= 0.02
Split Flow Ratio= 0.02
Log Output Level= 0
Friction Slope Method= 1
Unsteady Friction Slope Method= 2
Unsteady Bridges Friction Slope Method= 1
Parabolic Critical Depth
Global Vel Dist=  1 , 1 , 1
Global Log Level= 0
CheckData=True
Encroach Param= -1, 0, 0, 0
BEGIN DESCRIPTION:
Multiple Run
END DESCRIPTION:

--- Elm 65.f01 (steady flow) ---

Flow Title=Multiple
Number of Profiles=7
Profile Names=10-year,25-year,50-year,1pct_min,100-year,1pct_plu,500-year
River Rch & RM= Elm 65,Reach-1,1437
     102     134     159     118     189     260     269
Boundary for River Rch & Prof#=Elm 65,Reach-1,1
Up Type=0
Dn Type=3
Dn Slope=0.005
Boundary for River Rch & Prof#=Elm 65,Reach-1,2
Up Type=0
Dn Type=3
Dn Slope=0.005
Boundary for River Rch & Prof#=Elm 65,Reach-1,3
Up Type=0
Dn Type=3
Dn Slope=0.005
Boundary for River Rch & Prof#=Elm 65,Reach-1,4
Up Type=0
Dn Type=3
Dn Slope=0.005
Boundary for River Rch & Prof#=Elm 65,Reach-1,5
Up Type=0
Dn Type=3
Dn Slope=0.005
Boundary for River Rch & Prof#=Elm 65,Reach-1,6
Up Type=0
Dn Type=3
Dn Slope=0.005
Boundary for River Rch & Prof#=Elm 65,Reach-1,7
Up Type=0
Dn Type=3
Dn Slope=0.005

--- Elm 65.g01 (geometry) ---

Geom Title=Existing Conditions

River Reach=Elm 65,Reach-1
Reach XY= 30
      1522855.00      6777388.00      1522949.56      6777292.03
      1522996.85      6777244.05      1523003.45      6777227.36
      1523007.54      6777194.05      1523013.18      6777181.96
      1523099.15      6777090.29      1523109.19      6777039.74
      1523148.92      6776990.20      1523161.08      6776935.80
      1523198.90      6776890.19      1523210.85      6776835.71
      1523299.59      6776740.42      1523305.48      6776713.03
      1523303.73      6776648.48      1523296.58      6776631.83
      1523266.34      6776597.85      1523262.81      6776584.59
      1523274.33      6776567.98      1523331.88      6776511.47
      1523349.14      6776490.30      1523361.14      6776435.83
      1523394.15      6776397.61      1523402.63      6776381.95
      1523404.87      6776312.87      1523408.15      6776296.33
      1523416.72      6776289.98      1523448.46      6776285.28
      1523464.38      6776277.15      1523555.00      6776188.00

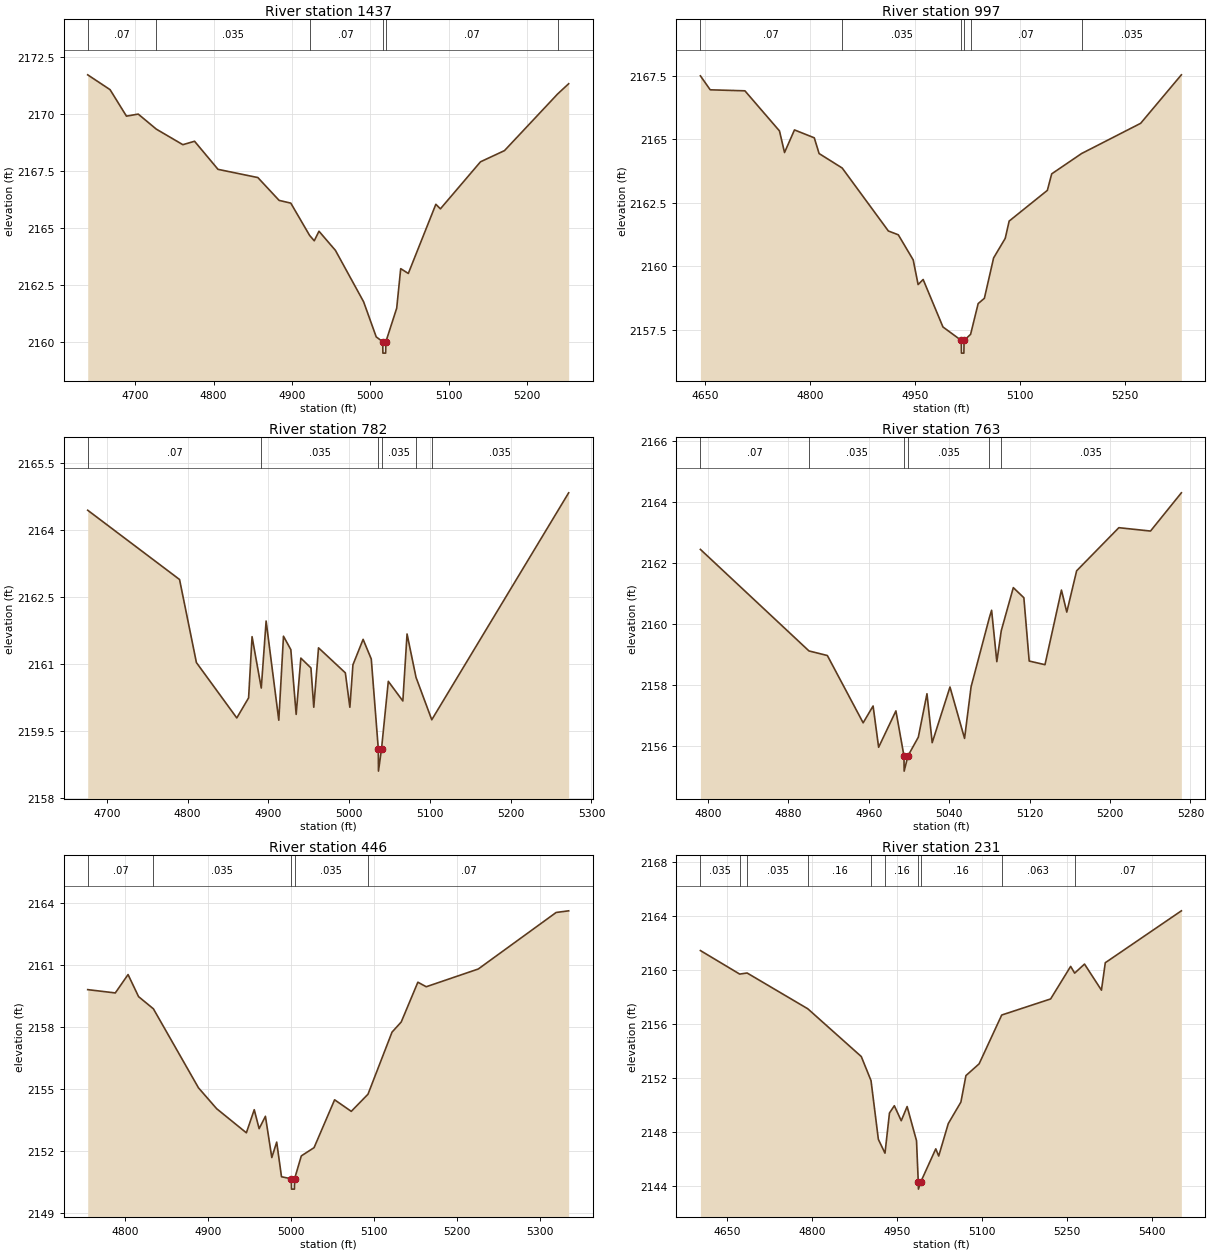
Type RM Length L Ch R = 1,1437,440,440,440
BEGIN DESCRIPTION:
467
END DESCRIPTION:
XS GIS Cut Line= 3
      1523105.00      6777638.00      1522902.28      6777340.02
      1522654.99      6777288.00
#Sta/Elev= 30
  4639.6 2171.71  4668.1 2171.06  4689.0 2169.90  4704.0 2169.99  4727.1 2169.33
  4760.9 2168.65  4775.8 2168.80  4805.7 2167.57  4856.5 2167.21  4883.6 2166.21
  4898.5 2166.09  4922.4 2164.68  4928.4 2164.44  4934.4 2164.86  4955.4 2164.02
  4991.3 2161.77  5007.4 2160.23  5015.7 2160.02  5015.9 2159.52  5019.4 2159.52
  5019.7 2160.02  5033.5 2161.49  5038.6 2163.22  5048.3 2163.01  5083.4 2166.04
  5089.2 2165.84  5140.3 2167.90  5170.9 2168.39  5238.6 2170.87  5252.7 2171.32
#Mann=6,-1,0
  4639.6    0.07       0  4727.1   0.035       0  4922.4    0.07       0
  5015.7    0.07       0  5019.7    0.07       0  5238.6   0.035       0
Bank Sta=5015.7,5019.7
Exp/Cntr=0.3,0.1

Type RM Length L Ch R = 1,997,215,215,215
BEGIN DESCRIPTION:
466
END DESCRIPTION:
XS GIS Cut Line= 3
      1523404.97      6777237.97      1523148.92      6776990.20
      1522854.99      6776837.99
#Sta/Elev= 30
  4643.7 2167.49  4657.7 2166.94  4707.3 2166.90  4756.7 2165.32  4763.9 2164.47
  4778.1 2165.36  4806.4 2165.05  4813.3 2164.43  4846.3 2163.86  4912.3 2161.38
  4926.5 2161.23  4947.8 2160.24  4954.8 2159.27  4962.0 2159.47  4990.3 2157.60
  5016.5 2157.07  5016.7 2156.57  5020.2 2156.57  5020.5 2157.07  5029.8 2157.31
  5040.6 2158.52  5049.5 2158.73  5062.7 2160.32  5079.3 2161.09  5084.9 2161.77
  5139.5 2162.98  5145.7 2163.63  5188.4 2164.43  5272.8 2165.62  5331.0 2167.53
#Mann=6,-1,0
  4643.7    0.07       0  4846.3   0.035       0  5016.5   0.035       0
  5020.5   0.035       0  5029.8    0.07       0  5188.4   0.035       0
Bank Sta=5016.5,5020.5
Exp/Cntr=0.3,0.1

Type RM Length L Ch R = 1,782,19,19,19
BEGIN DESCRIPTION:
792
END DESCRIPTION:
XS GIS Cut Line= 6
      1523467.97      6777024.32      1523344.87      6776859.92
      1523233.71      6776799.58      1523158.27      6776778.14
      1523128.90      6776788.46      1522974.89      6776789.26
#Sta/Elev= 30
  4676.3 2164.44  4790.0 2162.89  4810.9 2161.03  4860.9 2159.79  4875.5 2160.24
  4879.8 2161.61  4891.2 2160.46  4897.2 2161.96  4912.9 2159.74  4918.7 2161.62
  4927.8 2161.32  4934.4 2159.87  4940.2 2161.13  4952.7 2160.91  4956.2 2160.03
  4962.1 2161.36  4995.3 2160.80  5000.9 2160.03  5004.7 2160.98  5017.3 2161.55
  5027.4 2161.11  5036.1 2159.10  5036.3 2158.60  5040.1 2159.10  5048.5 2160.61
  5066.5 2160.17  5071.7 2161.67  5082.8 2160.70  5102.3 2159.75  5271.8 2164.83
#Mann=6,-1,0
  4676.3    0.07       0  4891.2   0.035       0  5036.1   0.035       0
  5040.1   0.035       0  5082.8    0.07       0  5102.3   0.035       0
Bank Sta=5036.1,5040.1
Exp/Cntr=0.3,0.1

Type RM Length L Ch R = 1,763,317,317,317
BEGIN DESCRIPTION:
791
END DESCRIPTION:
XS GIS Cut Line= 3
      1523441.36      6776878.35      1523253.02      6776789.22
      1522995.75      6776706.83
#Sta/Elev= 30
  4792.5 2162.44  4900.5 2159.12  4918.8 2158.97  4954.4 2156.77  4964.3 2157.32
  4969.8 2155.97  4987.0 2157.16  4995.0 2155.69  4995.2 2155.19  4999.0 2155.69
  5009.3 2156.30  5017.9 2157.72  5023.1 2156.12  5040.8 2157.94  5055.3 2156.26
  5061.8 2157.95  5080.0 2160.21  5082.2 2160.45  5087.4 2158.77  5091.8 2159.78
  5103.8 2161.19  5114.3 2160.86  5119.6 2158.79  5135.3 2158.67  5151.7 2161.11
  5157.0 2160.39  5166.8 2161.74  5208.8 2163.15  5240.3 2163.04  5271.0 2164.29
#Mann=6,-1,0
  4792.5    0.07       0  4900.5   0.035       0  4995.0   0.035       0
  4999.0   0.035       0  5080.0    0.07       0  5091.8   0.035       0
Bank Sta=4995,4999
Exp/Cntr=0.3,0.1

Type RM Length L Ch R = 1,446,215,215,215
BEGIN DESCRIPTION:
793
END DESCRIPTION:
XS GIS Cut Line= 3
      1523527.13      6776651.32      1523327.01      6776526.88
      1522983.98      6776491.57
#Sta/Elev= 30
  4754.5 2159.82  4787.8 2159.66  4803.2 2160.55  4815.9 2159.48  4833.8 2158.89
  4888.2 2155.06  4910.1 2154.05  4946.0 2152.88  4955.5 2154.00  4961.4 2153.08
  4969.0 2153.68  4976.7 2151.68  4982.6 2152.43  4988.4 2150.75  5000.2 2150.65
  5000.5 2150.15  5004.0 2150.15  5004.2 2150.65  5012.3 2151.76  5027.7 2152.16
  5052.5 2154.48  5072.6 2153.92  5092.8 2154.75  5121.8 2157.76  5132.9 2158.25
  5153.0 2160.18  5163.1 2159.96  5225.9 2160.82  5319.9 2163.56  5335.0 2163.64
#Mann=5,-1,0
  4754.5    0.07       0  4833.8   0.035       0  5000.2   0.035       0
  5004.2   0.035       0  5092.8    0.07       0
Bank Sta=5000.2,5004.2
Exp/Cntr=0.3,0.1

Type RM Length L Ch R = 1,231,183,183,183
BEGIN DESCRIPTION:
861
END DESCRIPTION:
XS GIS Cut Line= 4
      1523589.45      6776661.84      1523474.86      6776358.99
      1523315.26      6776313.98      1522979.82      6776444.88
#Sta/Elev= 30
  4602.6 2161.44  4672.0 2159.70  4685.1 2159.78  4792.4 2157.13  4886.8 2153.60
  4904.0 2151.82  4917.0 2147.47  4928.7 2146.45  4936.6 2149.42  4945.2 2149.96
  4957.4 2148.85  4967.8 2149.90  4984.4 2147.37  4987.5 2144.29  4987.8 2143.79
  4991.5 2144.29  5018.4 2146.77  5023.6 2146.24  5040.5 2148.64  5062.8 2150.23
  5071.7 2152.19  5095.0 2153.06  5134.9 2156.67  5221.3 2157.86  5256.7 2160.27
  5263.8 2159.77  5281.2 2160.44  5311.1 2158.51  5317.9 2160.54  5452.3 2164.38
#Mann=10,-1,0
  4602.6   0.035       0  4672.0    0.07       0  4685.1   0.035       0
  4792.4    0.16       0  4904.0    0.07       0  4928.7    0.16       0
  4987.5    0.07       0  4991.5    0.16       0  5134.9   0.063       0
  5263.8    0.07       0
Bank Sta=4987.5,4991.5
Exp/Cntr=0.3,0.1

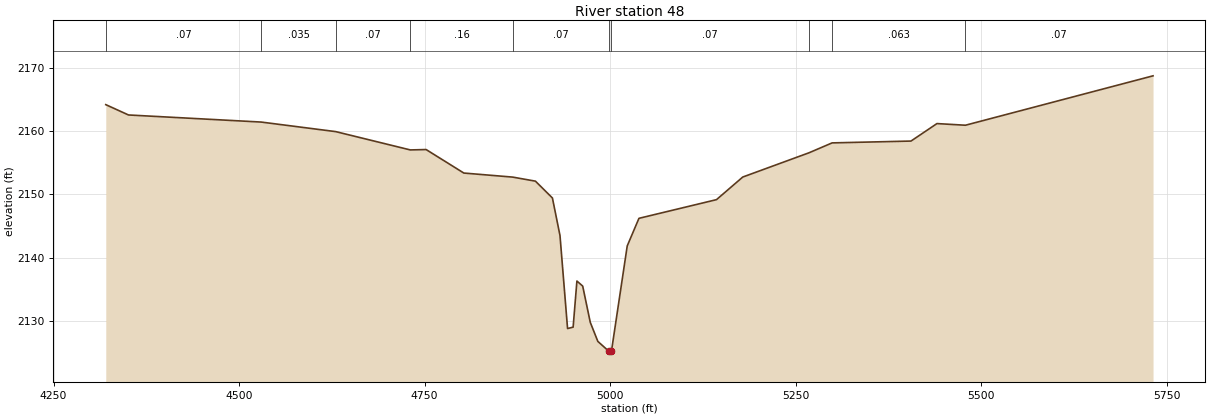
Type RM Length L Ch R = 1,48,0,0,0
BEGIN DESCRIPTION:
465
END DESCRIPTION:
XS GIS Cut Line= 4
      1523655.00      6776888.01      1523520.41      6776220.81
      1523453.14      6776195.59      1522842.84      6776443.73
#Sta/Elev= 30
  4320.4 2164.16  4351.0 2162.53  4529.8 2161.41  4630.3 2159.90  4730.8 2157.01
  4752.1 2157.07  4802.9 2153.36  4868.7 2152.72  4899.4 2152.08  4922.3 2149.42
  4932.5 2143.49  4942.7 2128.81  4950.2 2129.03  4955.3 2136.31  4963.1 2135.51
  4973.3 2129.79  4983.5 2126.78  4997.9 2125.27  4998.2 2124.77  5001.9 2125.27
  5023.1 2141.85  5038.9 2146.21  5143.4 2149.16  5178.8 2152.73  5268.1 2156.56
  5299.2 2158.12  5405.5 2158.41  5440.5 2161.17  5478.9 2160.91  5731.7 2168.71
#Mann=10,-1,0
  4320.4    0.07       0  4529.8   0.035       0  4630.3    0.07       0
  4730.8    0.16       0  4868.7    0.07       0  4997.9    0.07       0
  5001.9    0.07       0  5268.1    0.16       0  5299.2   0.063       0
  5478.9    0.07       0
Bank Sta=4997.9,5001.9
Exp/Cntr=0.3,0.1

Chan Stop Cuts=-1