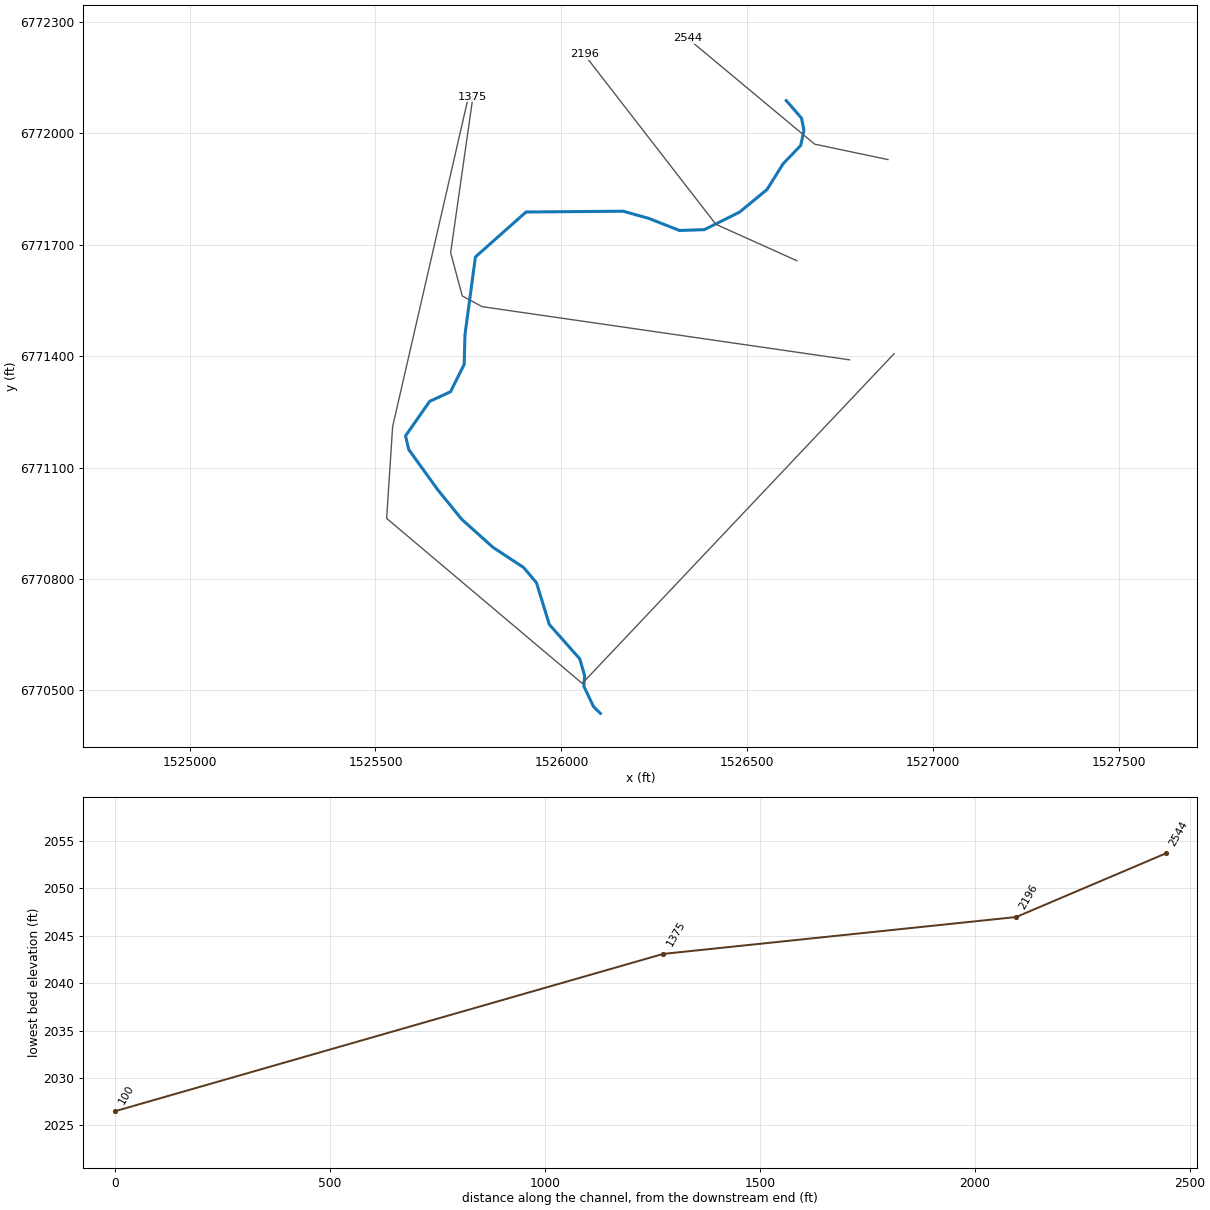
--- Elm 66.prj (project) ---

Proj Title=Elm 66 Base Level Engineering
Current Plan=p01
Default Exp/Contr=0.3,0.1
English Units
Geom File=g01
Flow File=f01
Plan File=p01
BEGIN DESCRIPTION:
Elm 66
END DESCRIPTION:

--- Elm 66.p01 (plan) ---

Plan Title=Multiple Run
Short Identifier=Multiple
Geom File=g01
Flow File=f01
Subcritical Flow
K Sum by GR= 0
Std Step Tol= 0.01
Critical Tol= 0.01
Num of Std Step Trials= 20
Max Error Tol= 0.3
Flow Tol Ratio= 0.001
Split Flow NTrial= 30
Split Flow Tol= 0.02
Split Flow Ratio= 0.02
Log Output Level= 0
Friction Slope Method= 1
Unsteady Friction Slope Method= 2
Unsteady Bridges Friction Slope Method= 1
Parabolic Critical Depth
Global Vel Dist=  1 , 1 , 1
Global Log Level= 0
CheckData=True
Encroach Param= -1, 0, 0, 0
BEGIN DESCRIPTION:
Multiple Run
END DESCRIPTION:

--- Elm 66.f01 (steady flow) ---

Flow Title=Multiple
Number of Profiles=7
Profile Names=10-year,25-year,50-year,1pct_min,100-year,1pct_plu,500-year
River Rch & RM= Elm 66,Reach-1,2544
     246     342     422     324     519     715     795
Boundary for River Rch & Prof#=Elm 66,Reach-1,1
Up Type=0
Dn Type=3
Dn Slope=0.005
Boundary for River Rch & Prof#=Elm 66,Reach-1,2
Up Type=0
Dn Type=3
Dn Slope=0.005
Boundary for River Rch & Prof#=Elm 66,Reach-1,3
Up Type=0
Dn Type=3
Dn Slope=0.005
Boundary for River Rch & Prof#=Elm 66,Reach-1,4
Up Type=0
Dn Type=3
Dn Slope=0.005
Boundary for River Rch & Prof#=Elm 66,Reach-1,5
Up Type=0
Dn Type=3
Dn Slope=0.005
Boundary for River Rch & Prof#=Elm 66,Reach-1,6
Up Type=0
Dn Type=3
Dn Slope=0.005
Boundary for River Rch & Prof#=Elm 66,Reach-1,7
Up Type=0
Dn Type=3
Dn Slope=0.005

--- Elm 66.g01 (geometry) ---

Geom Title=Existing Conditions

River Reach=Elm 66,Reach-1
Reach XY= 30
      1526605.00      6772088.00      1526646.02      6772040.86
      1526652.50      6772008.45      1526643.86      6771967.39
      1526596.32      6771917.70      1526553.11      6771848.55
      1526479.64      6771788.05      1526384.57      6771740.52
      1526317.59      6771738.36      1526235.48      6771770.77
      1526166.34      6771790.21      1525904.89      6771788.05
      1525768.77      6771667.05      1525740.68      6771457.46
      1525738.52      6771377.52      1525701.79      6771304.05
      1525645.61      6771278.13      1525580.79      6771185.21
      1525589.43      6771148.48      1525667.21      6771040.45
      1525732.04      6770960.50      1525816.30      6770884.88
      1525898.41      6770830.86      1525932.98      6770789.80
      1525967.55      6770677.45      1526049.66      6770584.54
      1526062.63      6770539.16      1526060.46      6770511.07
      1526086.68      6770455.82      1526105.00      6770438.00

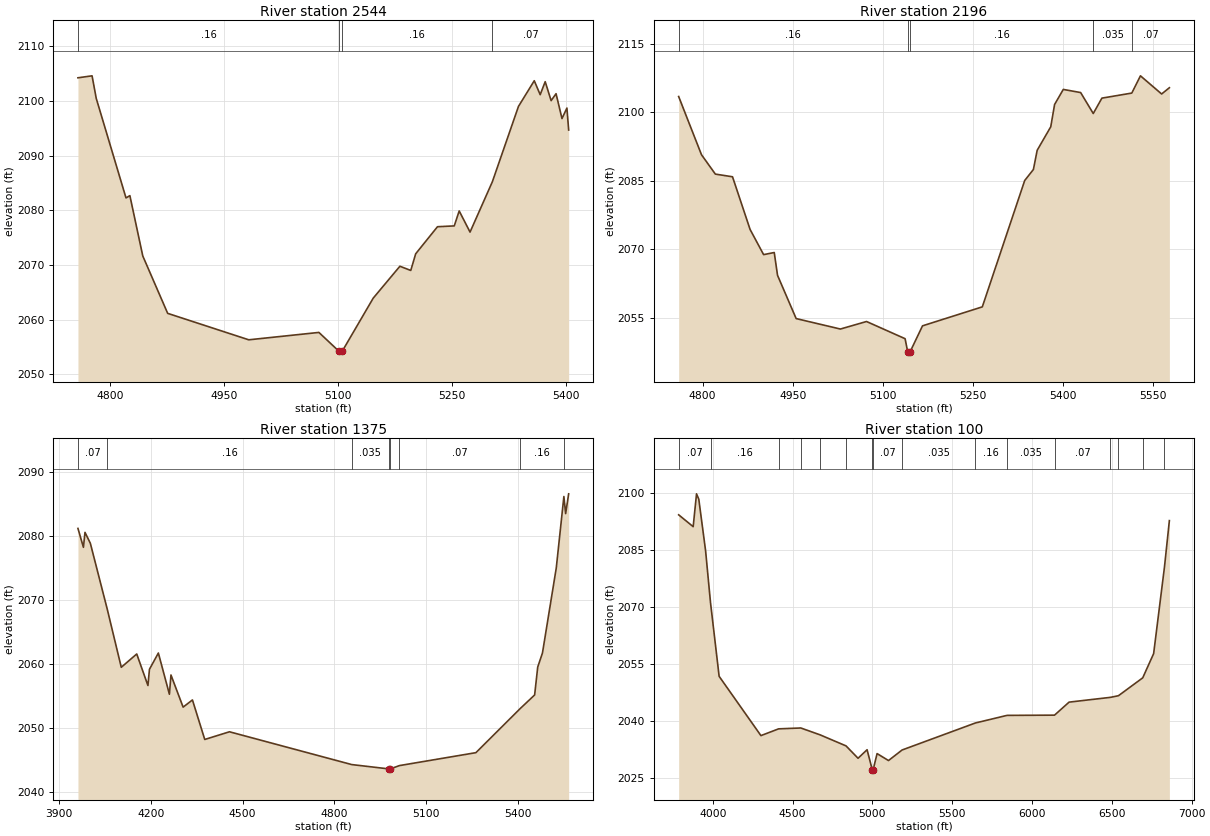
Type RM Length L Ch R = 1,2544,348,348,348
BEGIN DESCRIPTION:
385
END DESCRIPTION:
XS GIS Cut Line= 3
      1526878.57      6771929.23      1526681.44      6771970.76
      1526339.72      6772255.73
#Sta/Elev= 30
  4757.7 2104.25  4776.3 2104.61  4781.8 2100.48  4821.0 2082.27  4826.1 2082.69
  4843.1 2071.65  4875.9 2061.15  4982.7 2056.31  5075.1 2057.66  5101.7 2054.19
  5102.0 2053.69  5105.7 2054.19  5146.7 2063.94  5181.8 2069.77  5196.1 2069.00
  5202.6 2072.05  5231.3 2077.00  5253.4 2077.15  5259.9 2079.89  5274.2 2076.02
  5303.6 2085.23  5338.0 2099.02  5358.8 2103.71  5366.6 2101.16  5373.2 2103.54
  5381.0 2100.07  5387.5 2101.34  5395.3 2096.79  5401.8 2098.71  5404.1 2094.70
#Mann=4,-1,0
  4757.7    0.16       0  5101.7    0.07       0  5105.7    0.16       0
  5303.6    0.07       0
Bank Sta=5101.7,5105.7
Exp/Cntr=0.3,0.1

Type RM Length L Ch R = 1,2196,821,821,821
BEGIN DESCRIPTION:
795
END DESCRIPTION:
XS GIS Cut Line= 3
      1526633.49      6771656.92      1526415.63      6771754.95
      1526061.60      6772212.47
#Sta/Elev= 30
  4760.1 2103.44  4798.1 2090.69  4821.2 2086.44  4849.8 2085.85  4879.1 2074.30
  4901.6 2068.79  4919.3 2069.25  4924.8 2064.25  4955.8 2054.77  5029.5 2052.48
  5073.0 2054.13  5137.3 2050.36  5141.6 2047.48  5141.8 2046.98  5145.6 2047.48
  5166.3 2053.18  5265.9 2057.34  5336.5 2085.03  5351.0 2087.45  5357.3 2091.66
  5379.9 2096.81  5386.3 2101.70  5400.8 2105.00  5429.7 2104.31  5450.7 2099.72
  5465.1 2103.09  5514.9 2104.20  5529.3 2107.98  5564.6 2104.00  5577.5 2105.37
#Mann=5,-1,0
  4760.1    0.16       0  5141.6    0.07       0  5145.6    0.16       0
  5450.7   0.035       0  5514.9    0.07       0
Bank Sta=5141.6,5145.6
Exp/Cntr=0.3,0.1

Type RM Length L Ch R = 1,1375,1275,1275,1275
BEGIN DESCRIPTION:
794
END DESCRIPTION:
XS GIS Cut Line= 5
      1526775.10      6771390.05      1525786.80      6771533.21
      1525733.40      6771561.96      1525702.16      6771678.70
      1525762.07      6772098.03
#Sta/Elev= 30
  3962.2 2081.15  3980.1 2078.20  3985.2 2080.53  4002.7 2078.83  4057.9 2068.55
  4103.8 2059.46  4154.3 2061.54  4190.9 2056.62  4195.9 2059.15  4225.0 2061.69
  4261.1 2055.25  4266.2 2058.26  4305.9 2053.24  4336.4 2054.36  4376.6 2048.19
  4457.4 2049.39  4856.9 2044.27  4978.7 2043.59  4978.9 2043.09  4982.7 2043.59
  5012.8 2044.11  5262.8 2046.13  5407.4 2053.01  5454.7 2055.14  5464.8 2059.50
  5480.3 2061.70  5525.5 2075.00  5550.3 2086.13  5556.0 2083.46  5565.9 2086.55
#Mann=8,-1,0
  3962.2    0.07       0  4057.9    0.16       0  4856.9   0.035       0
  4978.7   0.035       0  4982.7   0.035       0  5012.8    0.07       0
  5407.4    0.16       0  5550.3    0.07       0
Bank Sta=4978.7,4982.7
Exp/Cntr=0.3,0.1

Type RM Length L Ch R = 1,100,0,0,0
BEGIN DESCRIPTION:
384
END DESCRIPTION:
XS GIS Cut Line= 5
      1526894.92      6771406.41      1526056.17      6770518.64
      1525530.00      6770963.00      1525546.08      6771210.20
      1525751.11      6772103.21
#Sta/Elev= 30
  3786.4 2094.29  3877.3 2091.17  3898.3 2099.82  3912.5 2098.40  3955.0 2084.86
  3985.9 2071.16  4039.9 2051.74  4301.7 2036.12  4412.5 2037.90  4551.4 2038.13
  4673.0 2036.31  4834.9 2033.41  4910.1 2030.15  4966.7 2032.40  4999.9 2027.00
  5000.2 2026.50  5003.9 2027.00  5029.4 2031.38  5100.9 2029.55  5186.0 2032.33
  5645.4 2039.45  5843.3 2041.45  6140.9 2041.51  6232.1 2044.94  6491.1 2046.20
  6541.3 2046.63  6693.4 2051.34  6761.8 2057.72  6829.5 2080.47  6860.4 2092.76
#Mann=16,-1,0
  3786.4    0.07       0  3985.9    0.16       0  4412.5   0.035       0
  4551.4    0.16       0  4673.0   0.035       0  4834.9    0.07       0
  4999.9    0.07       0  5003.9    0.07       0  5186.0   0.035       0
  5645.4    0.16       0  5843.3   0.035       0  6140.9    0.07       0
  6491.1    0.16       0  6541.3    0.07       0  6693.4    0.16       0
  6829.5    0.07       0
Bank Sta=4999.9,5003.9
Exp/Cntr=0.3,0.1

Chan Stop Cuts=-1