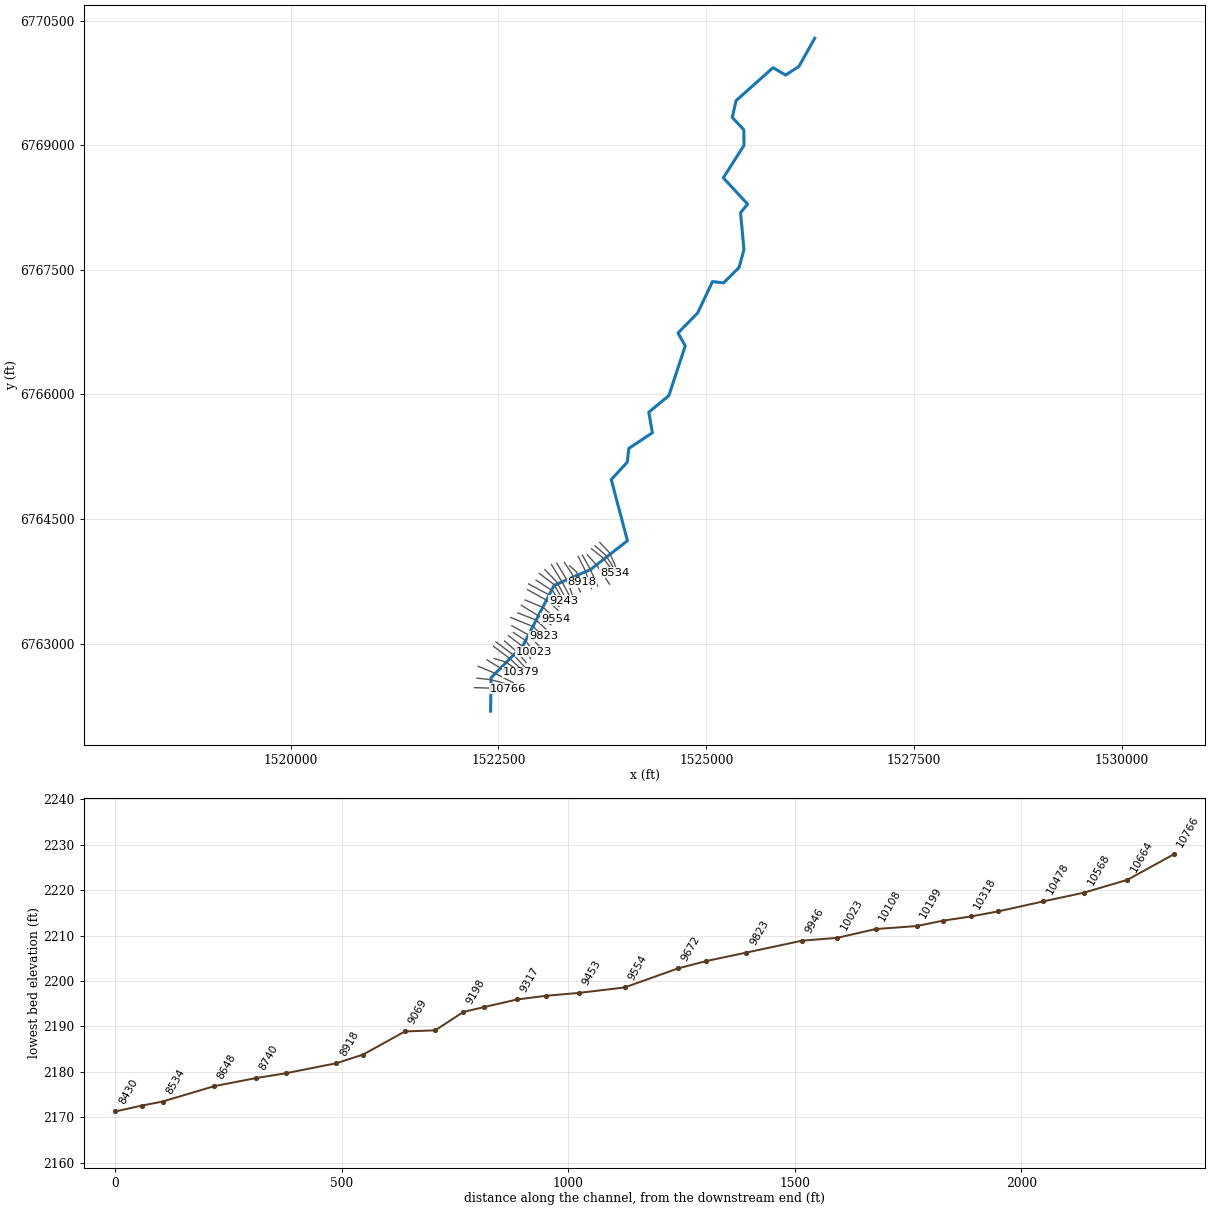
--- Elm 67.prj (project) ---

Proj Title=Elm 67 Base Level Engineering
Current Plan=p01
Default Exp/Contr=0.3,0.1
English Units
Geom File=g01
Flow File=f01
Plan File=p01
BEGIN DESCRIPTION:
Elm 67
END DESCRIPTION:

--- Elm 67.p01 (plan) ---

Plan Title=Multiple Run
Short Identifier=Multiple
Geom File=g01
Flow File=f01
Subcritical Flow
K Sum by GR= 0
Std Step Tol= 0.01
Critical Tol= 0.01
Num of Std Step Trials= 20
Max Error Tol= 0.3
Flow Tol Ratio= 0.001
Split Flow NTrial= 30
Split Flow Tol= 0.02
Split Flow Ratio= 0.02
Log Output Level= 0
Friction Slope Method= 1
Unsteady Friction Slope Method= 2
Unsteady Bridges Friction Slope Method= 1
Parabolic Critical Depth
Global Vel Dist=  1 , 1 , 1
Global Log Level= 0
CheckData=True
Encroach Param= -1, 0, 0, 0
BEGIN DESCRIPTION:
Multiple Run
END DESCRIPTION:

--- Elm 67.f01 (steady flow) ---

Flow Title=Multiple
Number of Profiles=7
Profile Names=10-year,25-year,50-year,1pct_min,100-year,1pct_plu,500-year
River Rch & RM= Elm 67,Reach-1,10766
     314     447     560     436     699     962    1100
Boundary for River Rch & Prof#=Elm 67,Reach-1,1
Up Type=0
Dn Type=3
Dn Slope=0.005
Boundary for River Rch & Prof#=Elm 67,Reach-1,2
Up Type=0
Dn Type=3
Dn Slope=0.005
Boundary for River Rch & Prof#=Elm 67,Reach-1,3
Up Type=0
Dn Type=3
Dn Slope=0.005
Boundary for River Rch & Prof#=Elm 67,Reach-1,4
Up Type=0
Dn Type=3
Dn Slope=0.005
Boundary for River Rch & Prof#=Elm 67,Reach-1,5
Up Type=0
Dn Type=3
Dn Slope=0.005
Boundary for River Rch & Prof#=Elm 67,Reach-1,6
Up Type=0
Dn Type=3
Dn Slope=0.005
Boundary for River Rch & Prof#=Elm 67,Reach-1,7
Up Type=0
Dn Type=3
Dn Slope=0.005

--- Elm 67.g01 (geometry) ---

Geom Title=Existing Conditions

River Reach=Elm 67,Reach-1
Reach XY= 30
      1522405.00      6762188.00      1522410.46      6762590.45
      1522796.84      6762981.95      1523168.45      6763701.63
      1523607.45      6763893.47      1524051.55      6764239.49
      1523856.42      6764975.85      1524049.53      6765185.55
      1524068.36      6765351.34      1524351.63      6765539.28
      1524308.46      6765786.52      1524549.48      6765985.56
      1524747.12      6766584.78      1524660.07      6766740.29
      1524896.86      6766981.94      1525074.77      6767359.02
      1525207.29      6767343.12      1525394.52      6767528.20
      1525453.14      6767744.13      1525412.37      6768188.09
      1525497.16      6768291.27      1525204.70      6768608.18
      1525453.95      6768998.44      1525451.46      6769186.54
      1525312.79      6769334.58      1525358.45      6769536.75
      1525802.71      6769932.93      1525955.00      6769845.10
      1526114.68      6769948.78      1526305.00      6770288.00

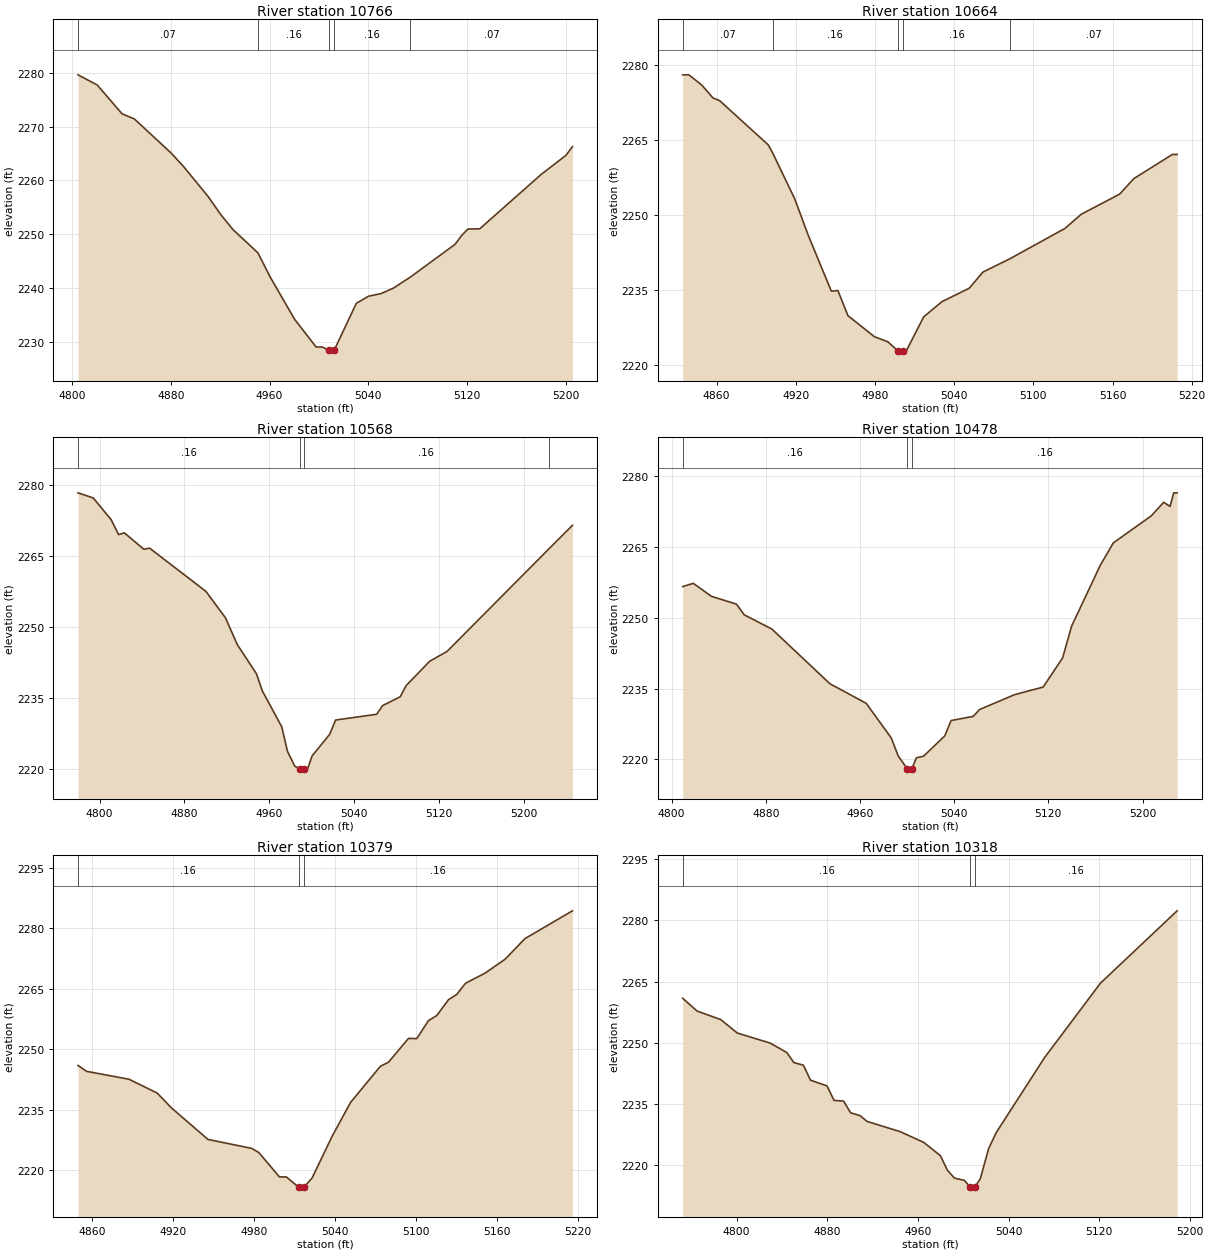
Type RM Length L Ch R = 1,10766,102,102,102
BEGIN DESCRIPTION:
Elm 67 10766.007
END DESCRIPTION:
XS GIS Cut Line= 3
      1522209.36      6762471.39      1522404.68      6762465.63
      1522610.22      6762460.98
#Sta/Elev= 30
  4804.6 2279.61  4820.2 2277.72  4840.3 2272.37  4850.3 2271.41  4880.3 2265.04
  4890.3 2262.54  4910.3 2256.94  4920.3 2253.66  4930.3 2250.85  4950.5 2246.53
  4960.3 2242.10  4980.3 2234.17  4997.7 2229.03  5002.7 2229.03  5008.3 2228.39
  5008.6 2227.89  5012.1 2227.89  5012.3 2228.39  5030.3 2237.14  5040.3 2238.47
  5050.3 2238.95  5060.3 2239.96  5074.1 2242.01  5110.4 2248.11  5115.9 2249.80
  5120.9 2250.96  5130.4 2250.99  5180.4 2261.13  5200.4 2264.65  5205.6 2266.27
#Mann=5,-1,0
  4804.6    0.07       0  4950.5    0.16       0  5008.3    0.07       0
  5012.3    0.16       0  5074.1    0.07       0
Bank Sta=5008.3,5012.3
Exp/Cntr=0.3,0.1

Type RM Length L Ch R = 1,10664,96,96,96
BEGIN DESCRIPTION:
Elm 67 10664.31
END DESCRIPTION:
XS GIS Cut Line= 3
      1522240.62      6762585.98      1522409.01      6762566.88
      1522606.95      6762513.05
#Sta/Elev= 30
  4834.3 2277.99  4839.0 2277.99  4848.8 2275.93  4857.3 2273.35  4862.3 2272.82
  4899.1 2263.98  4902.4 2262.39  4919.2 2253.16  4929.3 2245.96  4946.9 2234.70
  4951.9 2234.81  4959.5 2229.79  4979.6 2225.57  4989.7 2224.56  4997.2 2222.79
  4997.5 2222.29  5001.0 2222.29  5001.2 2222.79  5003.8 2222.79  5016.9 2229.55
  5030.7 2232.59  5051.4 2235.28  5061.8 2238.51  5082.3 2241.19  5124.0 2247.26
  5136.2 2250.07  5165.4 2254.12  5176.0 2257.20  5205.3 2262.06  5208.9 2262.06
#Mann=5,-1,0
  4834.3    0.07       0  4902.4    0.16       0  4997.2    0.07       0
  5001.2    0.16       0  5082.3    0.07       0
Bank Sta=4997.2,5001.2
Exp/Cntr=0.3,0.1

Type RM Length L Ch R = 1,10568,90,90,90
BEGIN DESCRIPTION:
Elm 67 10568.43
END DESCRIPTION:
XS GIS Cut Line= 3
      1522256.22      6762728.34      1522452.41      6762646.74
      1522678.12      6762530.41
#Sta/Elev= 30
  4779.7 2278.29  4794.1 2277.20  4810.9 2272.64  4818.0 2269.45  4823.4 2269.83
  4841.8 2266.36  4847.2 2266.60  4900.3 2257.47  4918.8 2251.87  4930.0 2246.19
  4948.0 2240.06  4953.5 2236.46  4971.9 2228.82  4977.3 2223.64  4984.2 2220.49
  4988.9 2219.96  4989.1 2219.46  4992.9 2219.96  4996.3 2219.96  5000.5 2222.67
  5017.1 2227.24  5022.7 2230.26  5061.4 2231.48  5067.0 2233.31  5083.6 2235.17
  5089.2 2237.52  5111.4 2242.68  5127.9 2244.78  5223.7 2266.40  5246.1 2271.42
#Mann=4,-1,0
  4779.7    0.16       0  4988.9    0.07       0  4992.9    0.16       0
  5223.7    0.07       0
Bank Sta=4988.9,4992.9
Exp/Cntr=0.3,0.1

Type RM Length L Ch R = 1,10478,99,99,99
BEGIN DESCRIPTION:
Elm 67 10478.37
END DESCRIPTION:
XS GIS Cut Line= 3
      1522360.36      6762806.48      1522530.53      6762702.30
      1522735.35      6762620.72
#Sta/Elev= 30
  4809.4 2256.65  4818.4 2257.34  4833.8 2254.59  4855.1 2252.93  4861.7 2250.66
  4885.2 2247.64  4934.5 2236.05  4965.3 2231.90  4986.6 2224.56  4992.5 2220.74
  5000.1 2218.03  5000.3 2217.53  5004.1 2218.03  5007.9 2220.35  5014.0 2220.69
  5032.0 2224.99  5037.4 2228.25  5056.2 2229.14  5061.6 2230.59  5091.3 2233.74
  5115.6 2235.35  5132.1 2241.51  5139.8 2248.28  5164.1 2261.15  5175.2 2265.91
  5207.5 2271.66  5218.0 2274.53  5223.4 2273.65  5226.5 2276.53  5229.4 2276.53
#Mann=3,-1,0
  4809.4    0.16       0  5000.1    0.07       0  5004.1    0.16       0
Bank Sta=5000.1,5004.1
Exp/Cntr=0.3,0.1

Type RM Length L Ch R = 1,10379,61,61,61
BEGIN DESCRIPTION:
Elm 67 10379.45
END DESCRIPTION:
XS GIS Cut Line= 3
      1522448.92      6762822.09      1522593.03      6762776.95
      1522770.05      6762653.73
#Sta/Elev= 30
  4849.3 2245.97  4855.7 2244.51  4887.1 2242.56  4908.0 2239.14  4918.5 2235.49
  4945.7 2227.65  4978.1 2225.43  4983.4 2224.41  4998.7 2218.36  5003.8 2218.36
  5012.9 2215.84  5013.1 2215.34  5016.6 2215.34  5016.9 2215.84  5022.9 2218.09
  5037.7 2228.38  5051.5 2236.84  5073.5 2245.75  5079.6 2246.79  5094.4 2252.67
  5100.5 2252.62  5109.3 2257.11  5115.4 2258.34  5124.1 2262.27  5130.2 2263.55
  5136.7 2266.33  5151.1 2268.82  5166.0 2272.27  5180.8 2277.39  5216.0 2284.27
#Mann=3,-1,0
  4849.3    0.16       0  5012.9    0.07       0  5016.9    0.16       0
Bank Sta=5012.9,5016.9
Exp/Cntr=0.3,0.1

Type RM Length L Ch R = 1,10318,62,62,62
BEGIN DESCRIPTION:
Elm 67 10317.66
END DESCRIPTION:
XS GIS Cut Line= 3
      1522438.51      6762969.66      1522631.23      6762825.56
      1522774.75      6762692.42
#Sta/Elev= 30
  4752.4 2260.94  4765.1 2257.81  4786.0 2255.72  4800.6 2252.43  4829.7 2249.96
  4844.3 2247.65  4850.6 2245.17  4858.9 2244.57  4865.2 2240.89  4879.8 2239.47
  4886.0 2235.93  4894.4 2235.77  4900.6 2232.91  4909.0 2232.19  4915.2 2230.78
  4944.4 2228.28  4965.2 2225.65  4979.8 2222.42  4986.1 2218.82  4992.3 2216.89
  5000.9 2216.38  5006.2 2214.71  5006.5 2214.21  5010.2 2214.71  5015.1 2216.76
  5022.4 2224.11  5029.2 2228.09  5071.8 2246.41  5121.1 2264.63  5188.8 2282.35
#Mann=3,-1,0
  4752.4    0.16       0  5006.2    0.07       0  5010.2    0.16       0
Bank Sta=5006.2,5010.2
Exp/Cntr=0.3,0.1

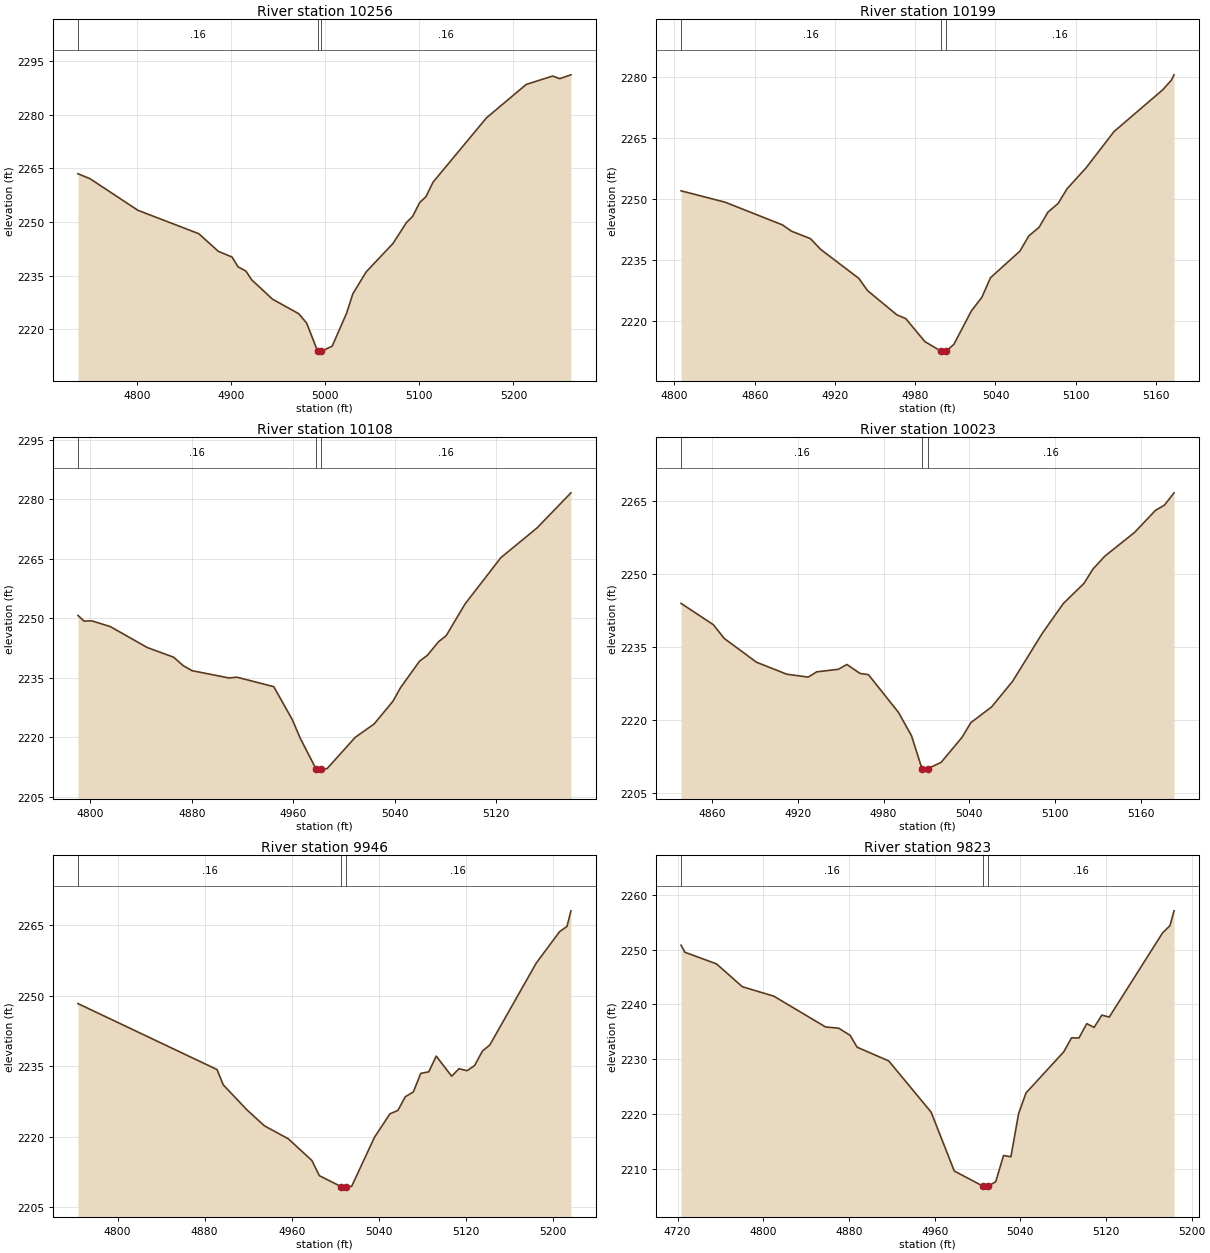
Type RM Length L Ch R = 1,10256,57,57,57
BEGIN DESCRIPTION:
Elm 67 10256.26
END DESCRIPTION:
XS GIS Cut Line= 3
      1522469.75      6763021.76      1522691.99      6762855.07
      1522856.83      6762672.88
#Sta/Elev= 30
  4737.6 2263.50  4750.4 2262.12  4801.3 2253.26  4865.9 2246.72  4886.7 2241.77
  4901.3 2240.17  4907.6 2237.44  4915.9 2236.27  4922.1 2233.80  4944.2 2228.38
  4972.1 2224.30  4980.5 2221.66  4992.2 2213.77  4992.4 2213.27  4996.2 2213.77
  5007.6 2215.24  5022.8 2224.41  5029.5 2229.87  5043.7 2236.03  5072.1 2243.96
  5086.3 2249.79  5093.0 2251.56  5100.5 2255.43  5107.2 2257.11  5114.7 2261.15
  5171.5 2279.18  5213.7 2288.52  5241.7 2290.86  5249.2 2290.13  5261.1 2291.20
#Mann=3,-1,0
  4737.6    0.16       0  4992.2    0.07       0  4996.2    0.16       0
Bank Sta=4992.2,4996.2
Exp/Cntr=0.3,0.1

Type RM Length L Ch R = 1,10199,91,91,91
BEGIN DESCRIPTION:
Elm 67 10199.09
END DESCRIPTION:
XS GIS Cut Line= 3
      1522572.23      6763032.14      1522718.03      6762907.16
      1522832.08      6762772.37
#Sta/Elev= 30
  4804.9 2252.08  4837.9 2249.27  4880.7 2243.69  4887.6 2242.12  4901.6 2240.31
  4909.2 2237.68  4937.8 2230.52  4944.4 2227.49  4966.3 2221.52  4972.9 2220.62
  4987.2 2214.95  4999.2 2212.61  4999.4 2212.11  5002.9 2212.11  5003.2 2212.61
  5008.9 2214.28  5022.0 2222.52  5029.8 2225.85  5036.3 2230.69  5058.3 2237.24
  5064.9 2240.97  5072.6 2243.10  5079.2 2246.81  5086.9 2249.00  5093.5 2252.58
  5107.8 2257.76  5128.6 2266.66  5164.9 2276.91  5171.5 2279.33  5173.5 2280.64
#Mann=3,-1,0
  4804.9    0.16       0  4999.2    0.07       0  5003.2    0.16       0
Bank Sta=4999.2,5003.2
Exp/Cntr=0.3,0.1

Type RM Length L Ch R = 1,10108,85,85,85
BEGIN DESCRIPTION:
Elm 67 10107.52
END DESCRIPTION:
XS GIS Cut Line= 3
      1522619.10      6763098.11      1522782.27      6762973.13
      1522886.15      6762822.51
#Sta/Elev= 30
  4790.3 2250.68  4795.1 2249.25  4801.4 2249.30  4815.9 2247.85  4844.9 2242.59
  4865.7 2240.15  4873.3 2238.01  4880.3 2236.75  4909.3 2234.92  4915.6 2235.11
  4944.6 2232.73  4959.2 2224.43  4965.5 2219.72  4978.0 2211.94  4978.2 2211.44
  4981.7 2211.44  4982.0 2211.94  4986.7 2212.09  5008.8 2219.95  5023.7 2223.32
  5038.5 2229.04  5044.6 2232.51  5059.5 2239.15  5065.6 2240.60  5074.4 2244.02
  5080.5 2245.58  5095.3 2253.54  5123.5 2265.21  5152.1 2272.73  5178.8 2281.57
#Mann=3,-1,0
  4790.3    0.16       0  4978.0    0.07       0  4982.0    0.16       0
Bank Sta=4978,4982
Exp/Cntr=0.3,0.1

Type RM Length L Ch R = 1,10023,77,77,77
BEGIN DESCRIPTION:
Elm 67 10023.06
END DESCRIPTION:
XS GIS Cut Line= 3
      1522679.81      6763134.61      1522822.20      6763040.84
      1522927.06      6762901.60
#Sta/Elev= 30
  4838.4 2243.92  4861.0 2239.54  4868.6 2236.73  4891.2 2231.84  4912.3 2229.39
  4927.3 2228.79  4933.3 2229.87  4948.4 2230.39  4954.4 2231.38  4963.5 2229.56
  4969.5 2229.28  4990.5 2221.54  4999.6 2216.75  5006.9 2210.00  5007.1 2209.50
  5010.9 2210.00  5020.3 2211.30  5034.9 2216.43  5041.1 2219.45  5055.7 2222.70
  5070.3 2227.94  5091.1 2237.79  5105.7 2243.87  5120.2 2248.02  5126.5 2250.97
  5134.8 2253.61  5155.6 2258.48  5170.2 2263.00  5176.5 2264.08  5183.2 2266.60
#Mann=3,-1,0
  4838.4    0.16       0  5006.9    0.07       0  5010.9    0.16       0
Bank Sta=5006.9,5010.9
Exp/Cntr=0.3,0.1

Type RM Length L Ch R = 1,9946,123,123,123
BEGIN DESCRIPTION:
Elm 67 9946.44
END DESCRIPTION:
XS GIS Cut Line= 3
      1522660.76      6763216.18      1522865.60      6763103.34
      1523014.38      6762942.45
#Sta/Elev= 30
  4763.6 2248.36  4891.4 2234.33  4897.1 2231.08  4918.9 2225.75  4935.0 2222.35
  4956.8 2219.61  4978.5 2215.00  4985.4 2211.76  5005.7 2209.39  5006.0 2208.89
  5009.7 2209.39  5015.1 2209.48  5036.1 2219.93  5050.3 2224.91  5057.6 2225.63
  5064.4 2228.54  5071.8 2229.57  5078.6 2233.51  5086.0 2233.85  5092.8 2237.19
  5107.0 2232.92  5113.8 2234.51  5121.1 2234.08  5128.0 2235.16  5135.3 2238.26
  5142.1 2239.57  5184.7 2256.97  5206.2 2263.67  5213.0 2264.78  5216.6 2268.09
#Mann=3,-1,0
  4763.6    0.16       0  5005.7    0.07       0  5009.7    0.16       0
Bank Sta=5005.7,5009.7
Exp/Cntr=0.3,0.1

Type RM Length L Ch R = 1,9823,89,89,89
BEGIN DESCRIPTION:
Elm 67 9823.28
END DESCRIPTION:
XS GIS Cut Line= 3
      1522648.62      6763315.13      1522914.21      6763207.50
      1523040.47      6763088.17
#Sta/Elev= 30
  4723.2 2250.79  4726.8 2249.50  4756.3 2247.38  4780.4 2243.21  4809.9 2241.48
  4858.1 2235.87  4870.4 2235.64  4881.1 2234.33  4887.6 2232.17  4917.1 2229.67
  4956.7 2220.32  4978.3 2209.58  5005.5 2206.77  5005.7 2206.27  5009.5 2206.77
  5017.0 2207.62  5024.3 2212.40  5031.2 2212.18  5038.4 2220.08  5045.3 2223.83
  5080.5 2231.32  5087.8 2233.88  5094.7 2233.85  5102.0 2236.47  5108.9 2235.79
  5116.1 2238.03  5123.0 2237.67  5172.8 2253.04  5179.7 2254.35  5183.5 2257.06
#Mann=3,-1,0
  4723.2    0.16       0  5005.5    0.07       0  5009.5    0.16       0
Bank Sta=5005.5,5009.5
Exp/Cntr=0.3,0.1

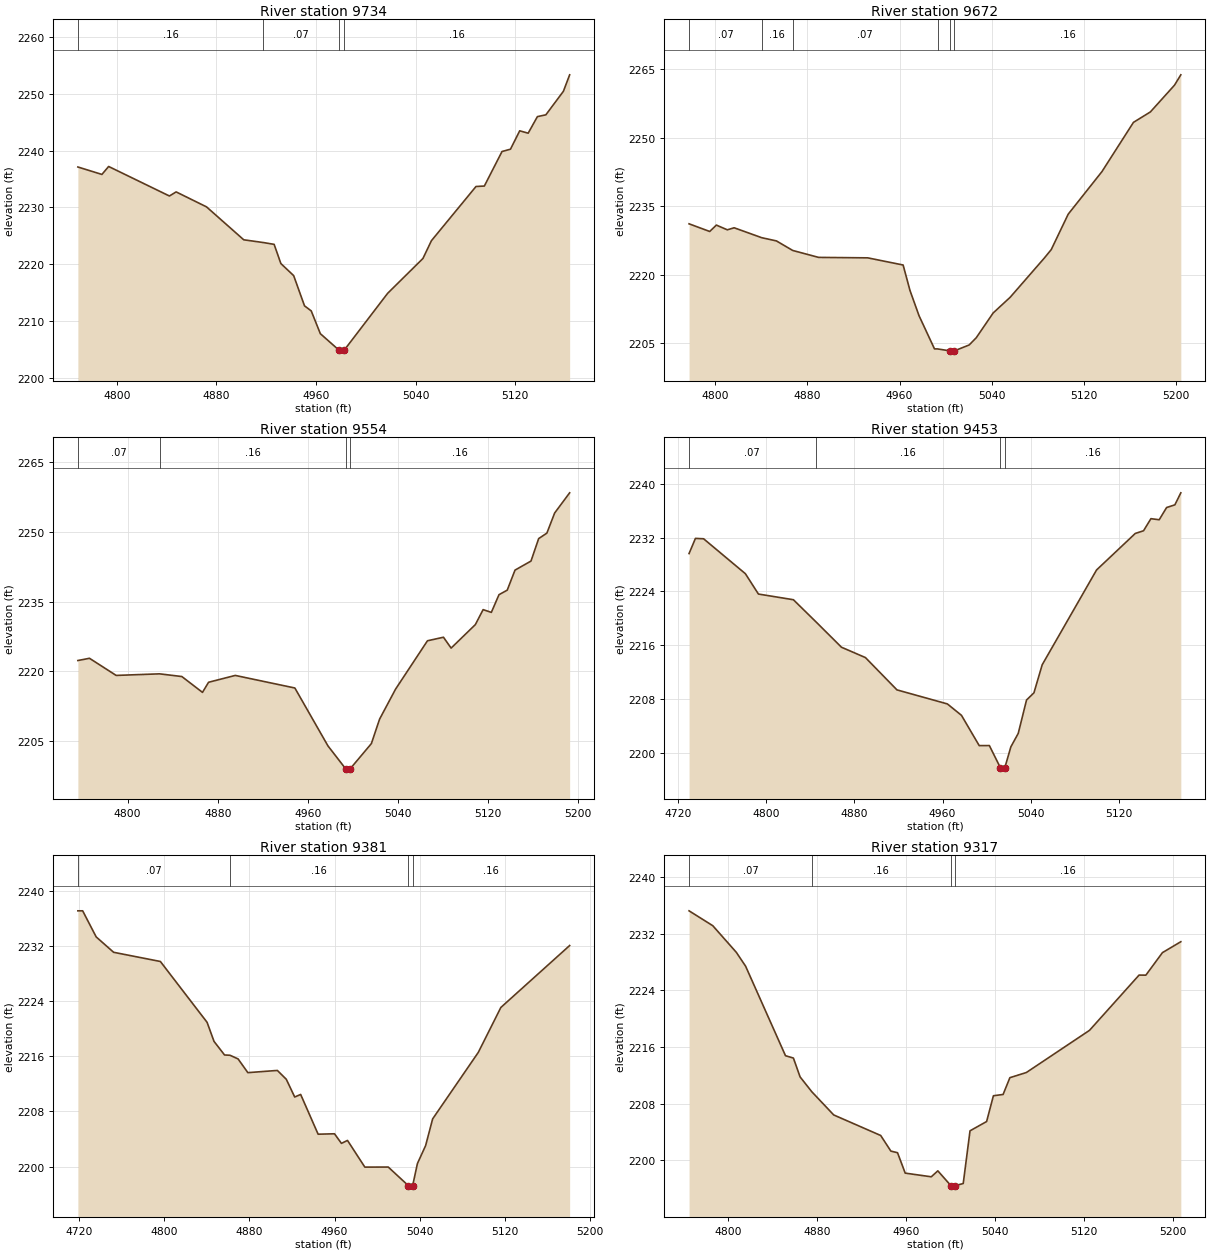
Type RM Length L Ch R = 1,9734,62,62,62
BEGIN DESCRIPTION:
Elm 67 9733.62
END DESCRIPTION:
XS GIS Cut Line= 3
      1522733.70      6763370.68      1522950.67      6763285.63
      1523070.20      6763176.50
#Sta/Elev= 30
  4768.8 2237.11  4788.1 2235.80  4793.5 2237.20  4842.3 2232.01  4847.7 2232.73
  4872.1 2230.10  4902.0 2224.31  4917.7 2223.83  4926.4 2223.51  4931.8 2220.14
  4942.1 2218.01  4950.8 2212.70  4956.2 2211.81  4963.5 2207.81  4978.6 2204.89
  4978.9 2204.39  4982.6 2204.89  5017.5 2214.89  5045.9 2221.03  5052.7 2224.15
  5088.5 2233.68  5095.2 2233.76  5109.4 2239.83  5116.2 2240.24  5123.6 2243.47
  5130.4 2243.05  5137.8 2245.96  5144.6 2246.28  5158.7 2250.42  5163.7 2253.31
#Mann=4,-1,0
  4768.8    0.16       0  4917.7    0.07       0  4978.6    0.07       0
  4982.6    0.16       0
Bank Sta=4978.6,4982.6
Exp/Cntr=0.3,0.1

Type RM Length L Ch R = 1,9672,118,118,118
BEGIN DESCRIPTION:
Elm 67 9671.61
END DESCRIPTION:
XS GIS Cut Line= 3
      1522775.33      6763462.71      1522966.30      6763344.66
      1523130.63      6763227.03
#Sta/Elev= 30
  4777.4 2231.12  4795.3 2229.44  4801.1 2230.84  4810.6 2229.80  4816.5 2230.25
  4840.4 2228.08  4853.2 2227.37  4867.3 2225.28  4889.8 2223.76  4932.4 2223.66
  4963.1 2222.09  4969.0 2216.55  4976.9 2210.98  4990.3 2203.71  4993.0 2203.70
  5003.6 2203.28  5003.9 2202.78  5007.6 2203.28  5020.4 2204.57  5026.5 2206.14
  5041.2 2211.58  5056.0 2215.03  5085.5 2223.59  5091.6 2225.47  5106.3 2233.23
  5135.6 2242.57  5162.9 2253.35  5177.6 2255.64  5198.5 2261.50  5204.0 2263.77
#Mann=6,-1,0
  4777.4    0.07       0  4840.4    0.16       0  4867.3    0.07       0
  4993.0    0.16       0  5003.6    0.07       0  5007.6    0.16       0
Bank Sta=5003.6,5007.6
Exp/Cntr=0.3,0.1

Type RM Length L Ch R = 1,9554,101,101,101
BEGIN DESCRIPTION:
Elm 67 9554.39
END DESCRIPTION:
XS GIS Cut Line= 3
      1522820.45      6763526.95      1523042.69      6763433.20
      1523185.06      6763299.51
#Sta/Elev= 30
  4755.8 2222.33  4766.1 2222.81  4789.8 2219.13  4828.3 2219.47  4848.1 2218.89
  4866.4 2215.49  4871.8 2217.66  4895.5 2219.13  4948.4 2216.43  4977.8 2203.99
  4993.5 2199.08  4993.8 2198.58  4997.5 2199.08  5016.3 2204.49  5023.6 2209.74
  5037.8 2216.19  5066.1 2226.57  5080.3 2227.33  5087.1 2225.00  5108.6 2230.04
  5115.5 2233.26  5122.8 2232.67  5129.6 2236.47  5136.9 2237.44  5143.8 2241.74
  5158.0 2243.69  5164.8 2248.51  5172.1 2249.69  5179.0 2254.01  5192.3 2258.34
#Mann=4,-1,0
  4755.8    0.07       0  4828.3    0.16       0  4993.5    0.07       0
  4997.5    0.16       0
Bank Sta=4993.5,4997.5
Exp/Cntr=0.3,0.1

Type RM Length L Ch R = 1,9453,72,72,72
BEGIN DESCRIPTION:
Elm 67 9453.45
END DESCRIPTION:
XS GIS Cut Line= 3
      1522849.94      6763650.23      1523086.09      6763520.00
      1523217.42      6763402.50
#Sta/Elev= 30
  4730.2 2229.62  4736.0 2231.87  4743.4 2231.81  4781.3 2226.63  4793.1 2223.62
  4824.8 2222.78  4844.9 2219.56  4868.4 2215.74  4890.1 2214.21  4918.7 2209.42
  4964.4 2207.34  4977.2 2205.65  4993.3 2201.16  5002.5 2201.17  5012.5 2197.88
  5012.7 2197.38  5016.5 2197.88  5022.0 2200.98  5028.7 2202.98  5036.2 2207.92
  5042.9 2208.98  5050.4 2213.14  5099.7 2227.19  5134.8 2232.60  5142.3 2233.00
  5149.0 2234.79  5156.5 2234.63  5163.2 2236.44  5170.7 2236.84  5176.1 2238.62
#Mann=4,-1,0
  4730.2    0.07       0  4844.9    0.16       0  5012.5    0.07       0
  5016.5    0.16       0
Bank Sta=5012.5,5016.5
Exp/Cntr=0.3,0.1

Type RM Length L Ch R = 1,9381,64,64,64
BEGIN DESCRIPTION:
Elm 67 9381.23
END DESCRIPTION:
XS GIS Cut Line= 3
      1522862.10      6763719.67      1523106.92      6763589.45
      1523226.69      6763448.85
#Sta/Elev= 30
  4718.9 2237.08  4723.4 2237.08  4736.1 2233.30  4752.5 2231.07  4796.4 2229.74
  4840.3 2220.92  4846.8 2218.16  4856.7 2216.19  4861.8 2216.15  4869.4 2215.62
  4878.6 2213.63  4906.3 2213.95  4914.7 2212.67  4922.6 2210.10  4928.2 2210.47
  4944.6 2204.71  4960.0 2204.77  4966.5 2203.38  4972.2 2203.81  4988.5 2199.94
  5010.5 2199.95  5029.4 2197.25  5029.6 2196.75  5033.4 2197.25  5037.9 2200.46
  5045.6 2203.06  5052.2 2206.93  5095.1 2216.57  5116.3 2223.08  5180.9 2232.05
#Mann=4,-1,0
  4718.9    0.07       0  4861.8    0.16       0  5029.4    0.07       0
  5033.4    0.16       0
Bank Sta=5029.4,5033.4
Exp/Cntr=0.3,0.1

Type RM Length L Ch R = 1,9317,74,74,74
BEGIN DESCRIPTION:
Elm 67 9317.33
END DESCRIPTION:
XS GIS Cut Line= 3
      1522952.43      6763764.78      1523152.06      6763634.59
      1523268.39      6763467.90
#Sta/Elev= 30
  4765.3 2235.22  4786.6 2233.12  4807.7 2229.37  4816.1 2227.40  4851.9 2214.77
  4859.0 2214.44  4865.0 2211.78  4875.5 2209.69  4895.2 2206.41  4937.4 2203.51
  4946.5 2201.31  4952.5 2201.08  4959.4 2198.20  4982.8 2197.68  4988.7 2198.52
  5000.4 2196.44  5000.7 2195.94  5004.4 2196.44  5011.5 2196.73  5017.6 2204.17
  5032.5 2205.48  5038.6 2209.12  5047.3 2209.30  5053.4 2211.67  5068.2 2212.40
  5124.9 2218.35  5169.4 2226.15  5175.5 2226.14  5190.4 2229.32  5206.9 2230.86
#Mann=4,-1,0
  4765.3    0.07       0  4875.5    0.16       0  5000.4    0.07       0
  5004.4    0.16       0
Bank Sta=5000.4,5004.4
Exp/Cntr=0.3,0.1

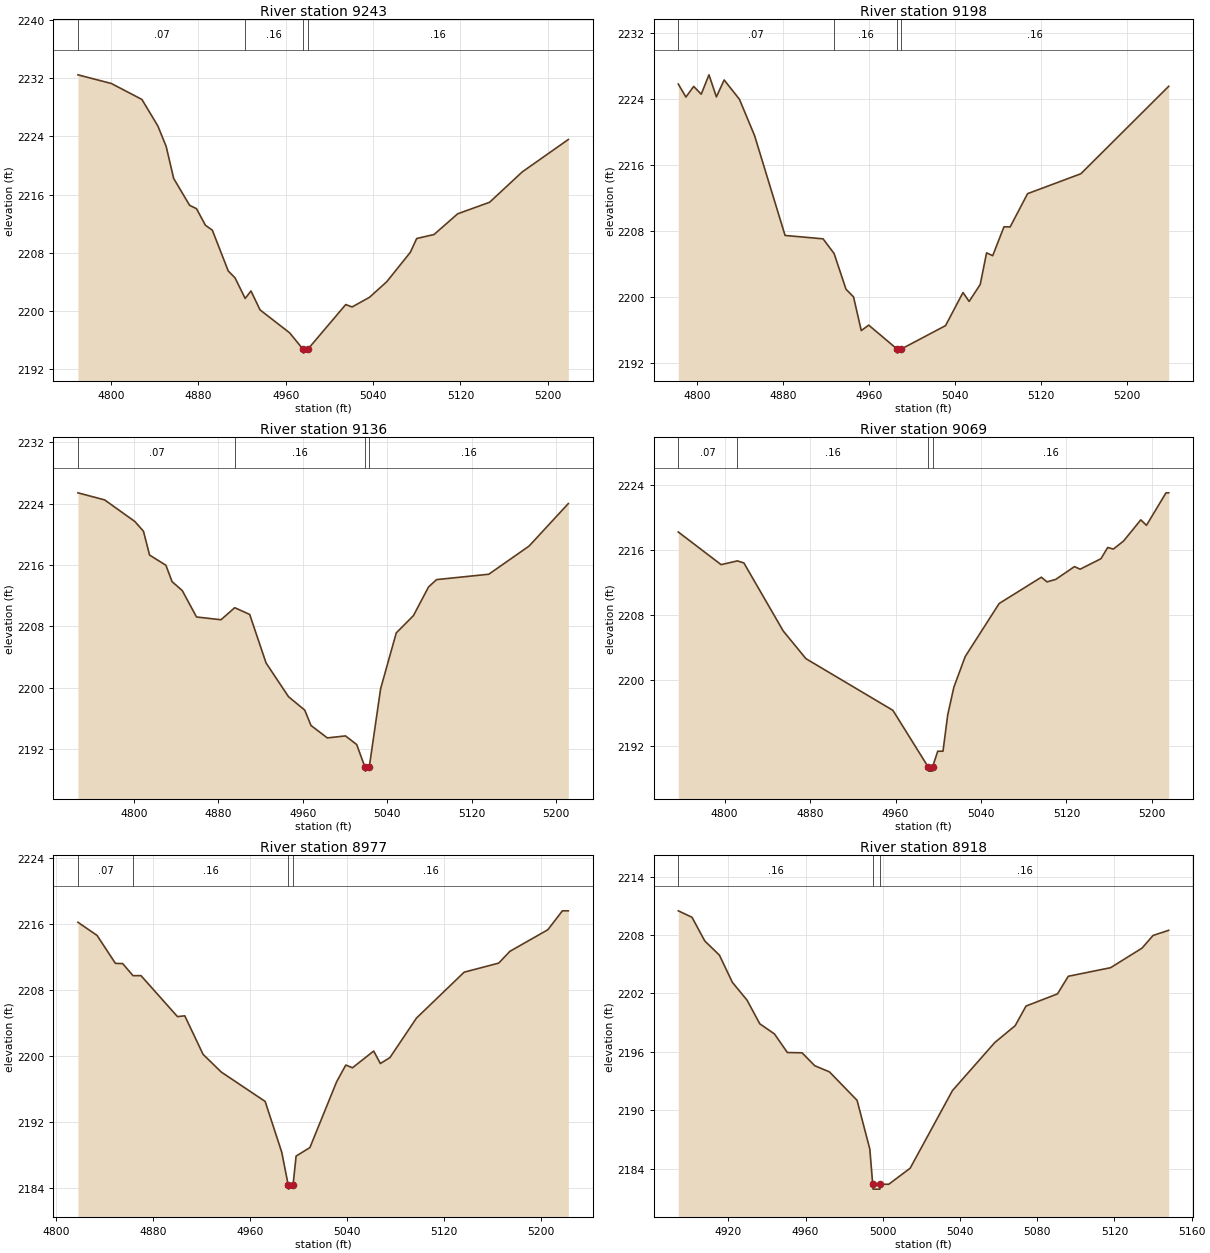
Type RM Length L Ch R = 1,9243,45,45,45
BEGIN DESCRIPTION:
Elm 67 9242.93
END DESCRIPTION:
XS GIS Cut Line= 3
      1522990.62      6763846.38      1523169.42      6763710.98
      1523280.26      6763515.27
#Sta/Elev= 30
  4769.6 2232.46  4800.2 2231.27  4828.2 2229.08  4842.8 2225.44  4850.4 2222.64
  4857.3 2218.23  4871.9 2214.54  4878.2 2214.08  4886.4 2211.80  4892.7 2211.13
  4907.3 2205.52  4913.5 2204.58  4922.8 2201.75  4928.1 2202.78  4936.4 2200.18
  4963.5 2197.03  4976.0 2194.74  4976.3 2194.24  4980.0 2194.74  5014.9 2200.91
  5020.7 2200.58  5036.6 2201.90  5052.5 2204.05  5074.1 2208.09  5079.9 2209.98
  5095.8 2210.53  5117.4 2213.37  5146.7 2214.96  5176.6 2219.13  5218.8 2223.58
#Mann=4,-1,0
  4769.6    0.07       0  4922.8    0.16       0  4976.0    0.07       0
  4980.0    0.16       0
Bank Sta=4976,4980
Exp/Cntr=0.3,0.1

Type RM Length L Ch R = 1,9198,62,62,62
BEGIN DESCRIPTION:
Elm 67 9198.01
END DESCRIPTION:
XS GIS Cut Line= 3
      1523058.32      6763891.52      1523202.41      6763742.23
      1523320.25      6763523.88
#Sta/Elev= 30
  4782.9 2225.76  4790.0 2224.19  4797.2 2225.48  4804.2 2224.53  4811.4 2226.88
  4818.3 2224.21  4825.5 2226.26  4839.7 2223.92  4853.8 2219.51  4882.1 2207.43
  4917.4 2207.02  4927.7 2205.23  4938.7 2200.92  4945.7 2199.99  4952.9 2195.91
  4959.8 2196.57  4986.1 2193.68  4986.4 2193.18  4990.1 2193.68  5031.2 2196.51
  5047.4 2200.52  5053.1 2199.44  5063.4 2201.49  5069.3 2205.32  5075.0 2204.98
  5085.5 2208.48  5091.2 2208.46  5107.4 2212.49  5156.9 2214.90  5238.5 2225.49
#Mann=4,-1,0
  4782.9    0.07       0  4927.7    0.16       0  4986.1    0.07       0
  4990.1    0.16       0
Bank Sta=4986.1,4990.1
Exp/Cntr=0.3,0.1

Type RM Length L Ch R = 1,9136,67,67,67
BEGIN DESCRIPTION:
Elm 67 9136.3
END DESCRIPTION:
XS GIS Cut Line= 3
      1523136.46      6763953.99      1523266.64      6763740.49
      1523368.14      6763551.25
#Sta/Elev= 30
  4746.9 2225.41  4772.2 2224.49  4800.8 2221.68  4809.0 2220.41  4814.8 2217.30
  4830.3 2215.97  4836.1 2213.84  4845.8 2212.67  4859.3 2209.23  4882.5 2208.87
  4895.5 2210.44  4909.7 2209.56  4925.2 2203.24  4946.5 2198.84  4961.9 2197.09
  4967.8 2195.09  4983.3 2193.47  5000.5 2193.73  5011.1 2192.61  5019.0 2189.64
  5019.3 2189.14  5023.0 2189.64  5033.8 2199.89  5048.6 2207.15  5064.9 2209.41
  5079.2 2213.14  5086.8 2214.10  5136.3 2214.80  5174.5 2218.47  5211.7 2224.01
#Mann=4,-1,0
  4746.9    0.07       0  4895.5    0.16       0  5019.0    0.07       0
  5023.0    0.16       0
Bank Sta=5019,5023
Exp/Cntr=0.3,0.1

Type RM Length L Ch R = 1,9069,92,92,92
BEGIN DESCRIPTION:
Elm 67 9069.45
END DESCRIPTION:
XS GIS Cut Line= 3
      1523200.67      6763969.66      1523327.41      6763761.32
      1523398.59      6763558.19
#Sta/Elev= 30
  4756.6 2218.19  4796.7 2214.19  4811.9 2214.65  4818.0 2214.40  4854.8 2206.07
  4876.1 2202.67  4957.5 2196.34  4990.6 2189.39  4990.9 2188.89  4994.4 2188.89
  4994.6 2189.39  4999.5 2191.33  5004.4 2191.33  5008.8 2195.76  5014.6 2199.18
  5025.2 2202.93  5057.0 2209.43  5096.5 2212.65  5101.8 2212.08  5109.9 2212.38
  5127.5 2213.95  5132.8 2213.63  5152.3 2214.92  5158.6 2216.29  5163.9 2216.10
  5173.5 2217.09  5189.6 2219.68  5194.9 2219.01  5213.2 2222.99  5215.7 2222.99
#Mann=4,-1,0
  4756.6    0.07       0  4811.9    0.16       0  4990.6    0.07       0
  4994.6    0.16       0
Bank Sta=4990.6,4994.6
Exp/Cntr=0.3,0.1

Type RM Length L Ch R = 1,8977,59,59,59
BEGIN DESCRIPTION:
Elm 67 8977.23
END DESCRIPTION:
XS GIS Cut Line= 3
      1523292.69      6763978.34      1523393.38      6763825.56
      1523485.40      6763624.16
#Sta/Elev= 30
  4818.3 2216.22  4834.1 2214.62  4849.2 2211.23  4855.2 2211.20  4863.7 2209.74
  4870.3 2209.74  4900.4 2204.76  4906.4 2204.86  4921.5 2200.18  4936.5 2198.03
  4972.7 2194.46  4986.4 2188.28  4991.7 2184.31  4992.0 2183.81  4995.7 2184.31
  4998.2 2187.82  5009.6 2188.86  5031.6 2196.84  5039.2 2198.88  5044.7 2198.55
  5062.2 2200.58  5067.7 2199.06  5075.6 2199.79  5097.5 2204.59  5136.8 2210.16
  5165.3 2211.26  5174.5 2212.69  5205.8 2215.31  5217.8 2217.61  5222.7 2217.61
#Mann=4,-1,0
  4818.3    0.07       0  4863.7    0.16       0  4991.7    0.07       0
  4995.7    0.16       0
Bank Sta=4991.7,4995.7
Exp/Cntr=0.3,0.1

Type RM Length L Ch R = 1,8918,112,112,112
BEGIN DESCRIPTION:
Elm 67 8917.886
END DESCRIPTION:
XS GIS Cut Line= 3
      1523355.02      6763937.99      1523434.84      6763868.39
      1523505.01      6763737.97
#Sta/Elev= 30
  4894.1 2210.48  4901.2 2209.82  4907.8 2207.39  4915.4 2205.93  4922.1 2203.14
  4929.7 2201.31  4936.3 2198.88  4943.9 2197.84  4950.6 2195.93  4958.2 2195.90
  4964.8 2194.57  4972.4 2193.94  4986.7 2191.02  4993.3 2186.01  4994.8 2182.40
  4995.0 2181.90  4998.5 2181.90  4998.8 2182.40  5003.1 2182.40  5014.2 2184.05
  5036.1 2192.02  5058.0 2196.95  5068.6 2198.69  5074.2 2200.70  5090.5 2201.95
  5096.1 2203.76  5118.0 2204.64  5134.3 2206.65  5140.0 2207.95  5148.1 2208.48
#Mann=3,-1,0
  4894.1    0.16       0  4994.8    0.07       0  4998.8    0.16       0
Bank Sta=4994.8,4998.8
Exp/Cntr=0.3,0.1

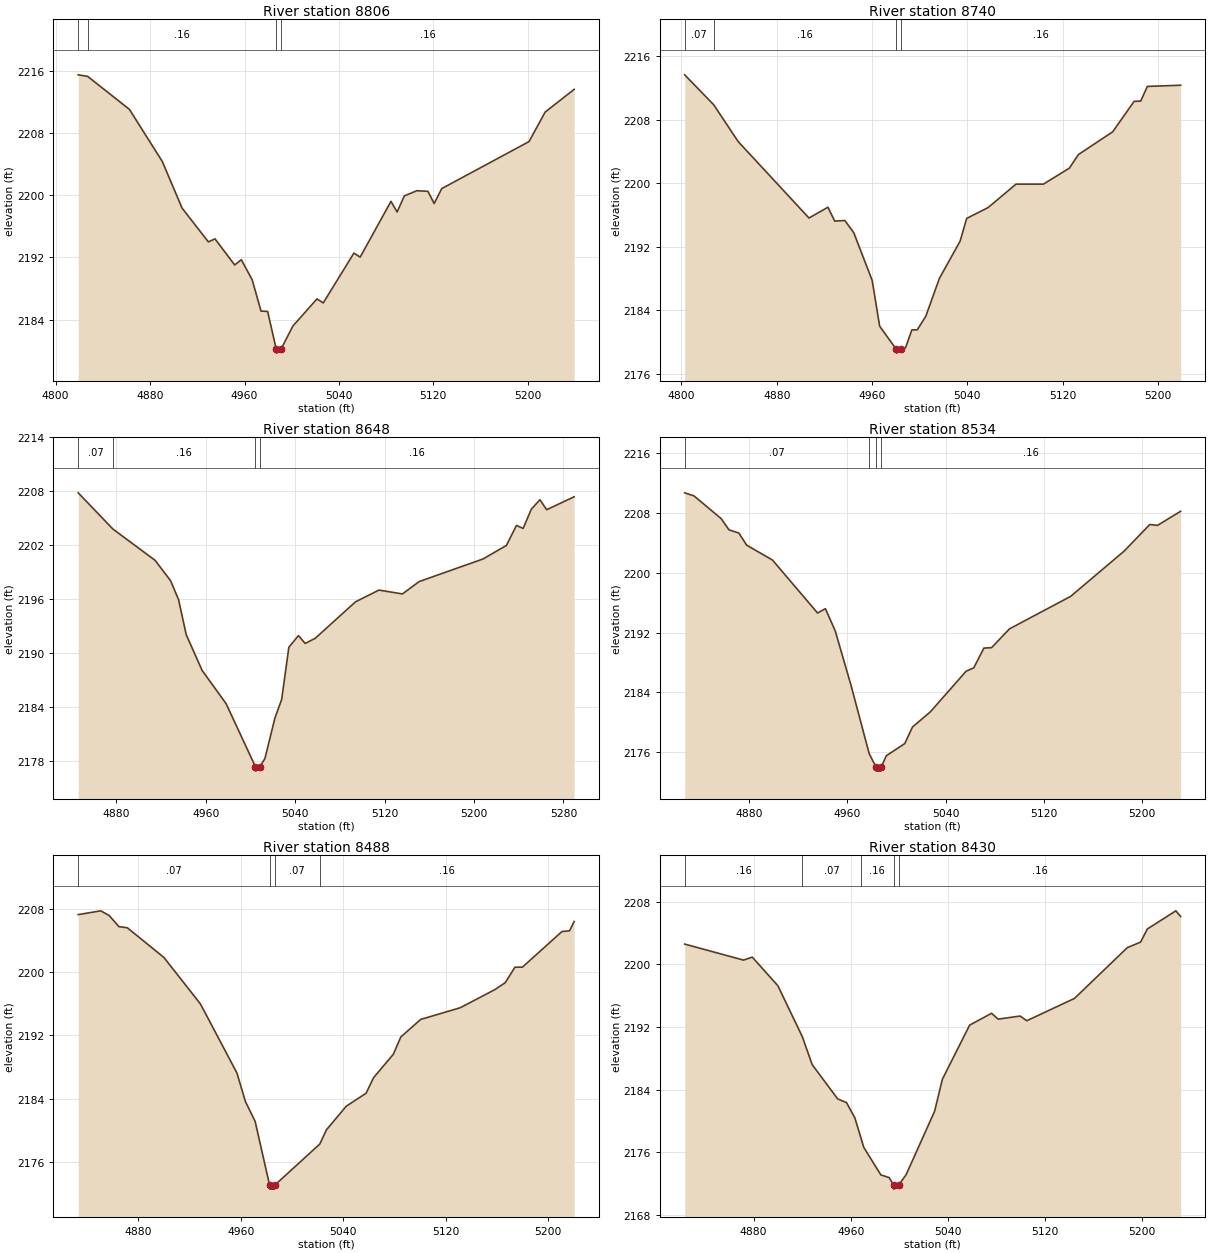
Type RM Length L Ch R = 1,8806,66,66,66
BEGIN DESCRIPTION:
Elm 67 8806.19
END DESCRIPTION:
XS GIS Cut Line= 3
      1523459.33      6764049.56      1523542.69      6763884.59
      1523618.67      6763661.82
#Sta/Elev= 30
  4819.1 2215.51  4827.1 2215.31  4862.5 2211.06  4890.4 2204.34  4907.1 2198.35
  4929.4 2194.00  4935.0 2194.39  4951.7 2191.03  4957.3 2191.71  4966.5 2189.12
  4974.0 2185.09  4979.6 2185.05  4986.9 2180.18  4987.2 2179.68  4990.9 2180.18
  5001.0 2183.17  5021.4 2186.66  5026.7 2186.14  5052.7 2192.56  5058.0 2192.04
  5084.1 2199.22  5089.3 2197.85  5095.4 2199.92  5106.0 2200.59  5115.4 2200.51
  5120.7 2198.94  5127.1 2200.86  5201.1 2206.92  5214.7 2210.71  5239.3 2213.64
#Mann=4,-1,0
  4819.1    0.07       0  4827.1    0.16       0  4986.9    0.07       0
  4990.9    0.16       0
Bank Sta=4986.9,4990.9
Exp/Cntr=0.3,0.1

Type RM Length L Ch R = 1,8740,92,92,92
BEGIN DESCRIPTION:
Elm 67 8740.47
END DESCRIPTION:
XS GIS Cut Line= 3
      1523509.68      6764065.17      1523605.19      6763895.00
      1523693.48      6763692.45
#Sta/Elev= 30
  4802.8 2213.68  4827.1 2209.92  4847.7 2205.27  4907.1 2195.64  4923.0 2197.00
  4928.7 2195.25  4937.2 2195.33  4944.7 2193.78  4960.1 2187.79  4966.4 2182.01
  4980.3 2179.12  4980.6 2178.62  4984.3 2179.12  4988.1 2179.30  4993.4 2181.55
  4997.9 2181.55  5005.1 2183.26  5016.5 2188.03  5033.9 2192.73  5039.4 2195.59
  5057.4 2196.96  5080.8 2199.91  5103.8 2199.91  5125.6 2201.93  5133.1 2203.63
  5161.9 2206.50  5179.9 2210.34  5185.4 2210.37  5191.0 2212.22  5218.9 2212.37
#Mann=4,-1,0
  4802.8    0.07       0  4827.1    0.16       0  4980.3    0.07       0
  4984.3    0.16       0
Bank Sta=4980.3,4984.3
Exp/Cntr=0.3,0.1

Type RM Length L Ch R = 1,8648,114,114,114
BEGIN DESCRIPTION:
Elm 67 8648.18
END DESCRIPTION:
XS GIS Cut Line= 3
      1523568.74      6764068.60      1523679.84      6763948.82
      1523836.09      6763716.19
#Sta/Elev= 30
  4846.0 2207.83  4877.0 2203.80  4914.8 2200.31  4928.7 2198.03  4935.8 2195.92
  4942.6 2192.04  4956.8 2188.06  4978.3 2184.35  5004.5 2177.34  5004.8 2176.84
  5008.5 2177.34  5013.0 2178.24  5022.0 2182.77  5028.0 2184.83  5034.4 2190.63
  5043.0 2191.93  5049.0 2191.06  5058.0 2191.63  5094.0 2195.69  5115.0 2197.00
  5136.0 2196.57  5151.0 2197.95  5208.0 2200.46  5229.0 2201.97  5238.0 2204.20
  5244.0 2203.87  5251.3 2206.01  5259.0 2207.06  5265.0 2205.95  5289.6 2207.39
#Mann=4,-1,0
  4846.0    0.07       0  4877.0    0.16       0  5004.5    0.07       0
  5008.5    0.16       0
Bank Sta=5004.5,5008.5
Exp/Cntr=0.3,0.1

Type RM Length L Ch R = 1,8534,46,46,46
BEGIN DESCRIPTION:
Elm 67 8534.44
END DESCRIPTION:
XS GIS Cut Line= 3
      1523619.04      6764143.30      1523754.49      6764035.63
      1523894.61      6763852.27
#Sta/Elev= 30
  4827.6 2210.71  4835.2 2210.30  4857.3 2207.26  4863.7 2205.75  4871.7 2205.33
  4878.1 2203.70  4899.1 2201.71  4935.8 2194.62  4942.2 2195.20  4950.2 2192.22
  4963.0 2184.96  4977.8 2175.81  4983.5 2173.95  4983.7 2173.45  4987.2 2173.45
  4987.5 2173.95  4991.8 2175.51  5006.8 2177.14  5013.1 2179.36  5027.6 2181.38
  5056.7 2186.82  5063.0 2187.28  5071.2 2189.92  5077.5 2189.98  5092.0 2192.49
  5141.9 2196.85  5185.5 2202.92  5206.3 2206.47  5212.6 2206.35  5231.4 2208.24
#Mann=4,-1,0
  4827.6    0.07       0  4977.8    0.16       0  4983.5    0.07       0
  4987.5    0.16       0
Bank Sta=4983.5,4987.5
Exp/Cntr=0.3,0.1

Type RM Length L Ch R = 1,8488,58,58,58
BEGIN DESCRIPTION:
Elm 67 8488.28
END DESCRIPTION:
XS GIS Cut Line= 3
      1523660.74      6764177.99      1523792.69      6764063.41
      1523903.20      6763882.09
#Sta/Elev= 30
  4833.2 2207.29  4850.8 2207.77  4857.4 2207.17  4865.0 2205.77  4871.6 2205.62
  4900.1 2201.87  4928.6 2195.99  4957.1 2187.25  4963.7 2183.65  4971.3 2181.13
  4982.6 2173.06  4982.9 2172.56  4986.4 2172.56  4986.6 2173.06  5021.8 2178.27
  5026.9 2180.05  5042.4 2183.05  5057.9 2184.69  5063.7 2186.65  5079.2 2189.63
  5085.0 2191.81  5100.5 2194.03  5131.4 2195.51  5158.6 2197.82  5166.5 2198.68
  5174.1 2200.64  5179.9 2200.64  5210.8 2205.15  5216.7 2205.24  5220.3 2206.42
#Mann=4,-1,0
  4833.2    0.07       0  4982.6    0.07       0  4986.6    0.07       0
  5021.8    0.16       0
Bank Sta=4982.6,4986.6
Exp/Cntr=0.3,0.1

Type RM Length L Ch R = 1,8430,109,109,109
BEGIN DESCRIPTION:
Elm 67 8430.08
END DESCRIPTION:
XS GIS Cut Line= 3
      1523718.06      6764219.63      1523837.82      6764092.92
      1523930.80      6763877.70
#Sta/Elev= 30
  4823.2 2202.61  4871.7 2200.56  4878.9 2200.94  4900.0 2197.29  4920.2 2190.76
  4928.3 2187.20  4949.3 2182.82  4956.6 2182.34  4963.5 2180.39  4968.4 2177.87
  4970.8 2176.63  4984.9 2173.10  4991.8 2172.75  4995.5 2171.78  4995.7 2171.28
  4999.5 2171.78  5005.7 2173.12  5029.2 2181.23  5035.6 2185.32  5058.1 2192.25
  5076.2 2193.76  5081.6 2193.01  5099.7 2193.41  5105.2 2192.81  5144.5 2195.66
  5188.1 2202.16  5199.0 2202.86  5204.6 2204.54  5228.1 2206.86  5232.0 2206.14
#Mann=5,-1,0
  4823.2    0.16       0  4920.2    0.07       0  4968.4    0.16       0
  4995.5    0.07       0  4999.5    0.16       0
Bank Sta=4995.5,4999.5
Exp/Cntr=0.3,0.1