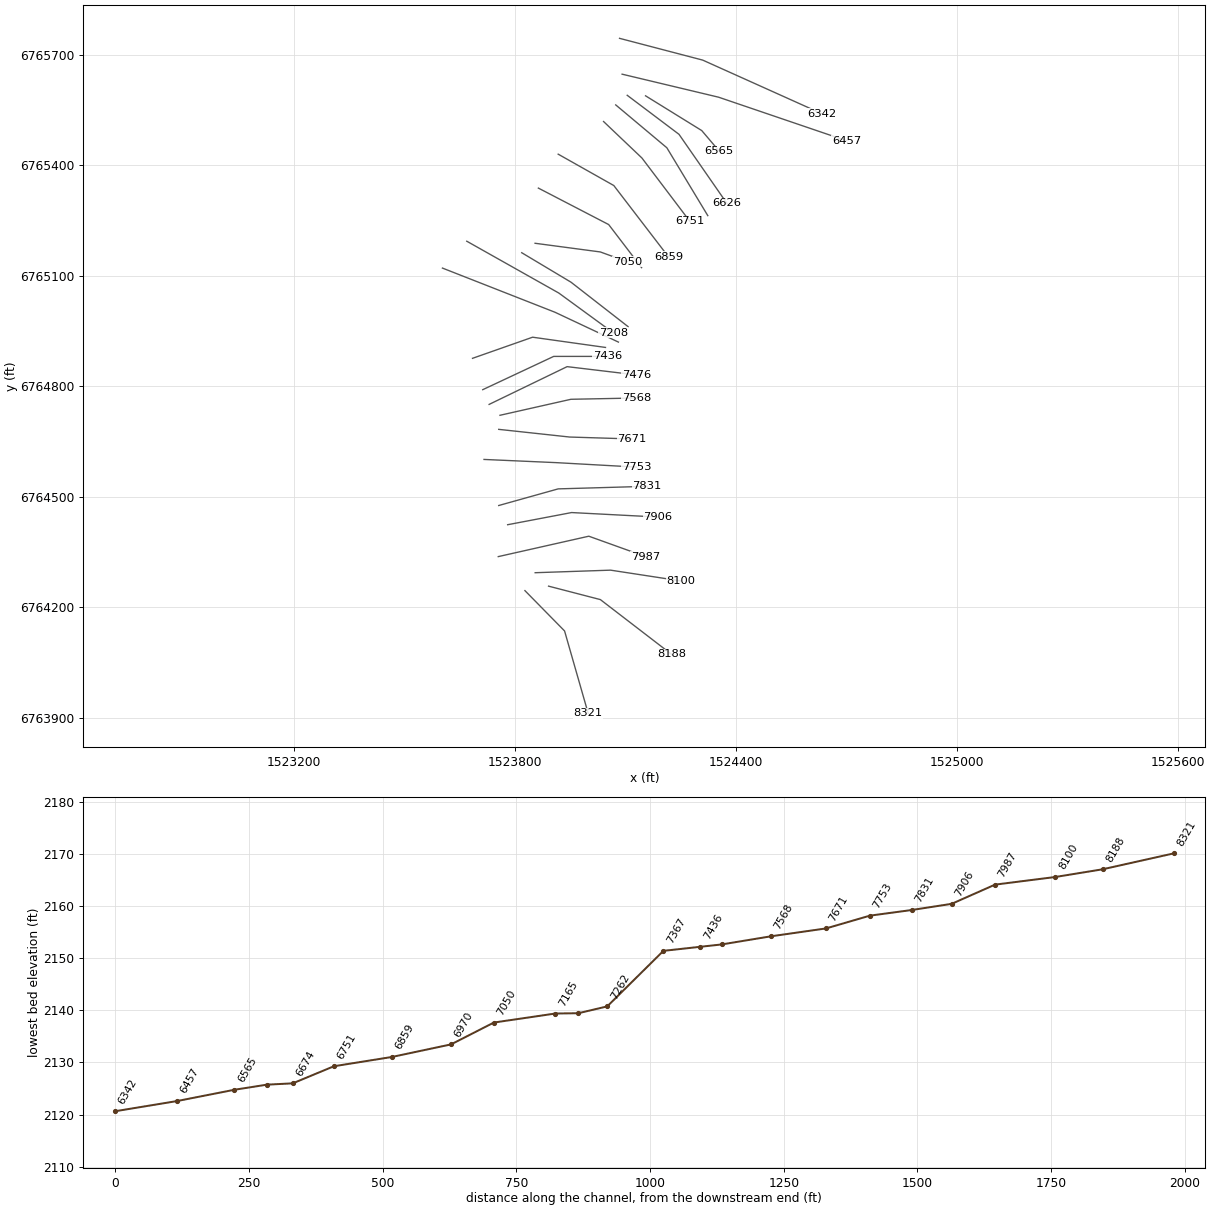
HEC-RAS study Elm 67.prj: Elm 67 Base Level Engineering

--- Elm 67.g01 (geometry) --- (continued)

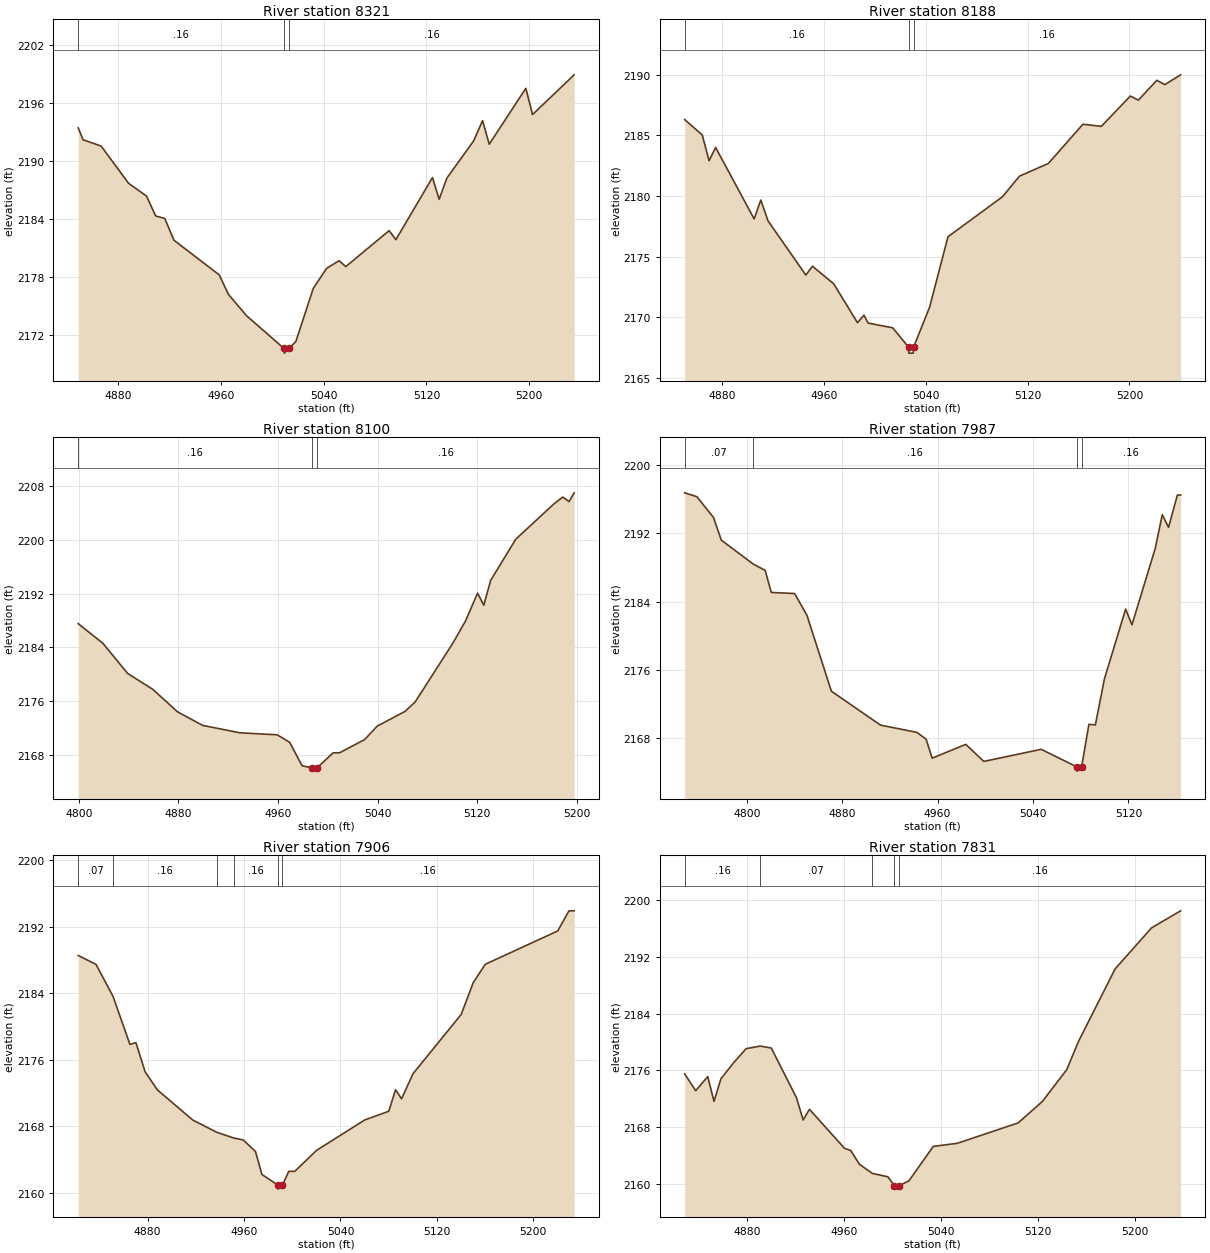
Type RM Length L Ch R = 1,8321,133,133,133
BEGIN DESCRIPTION:
Elm 67 8320.91
END DESCRIPTION:
XS GIS Cut Line= 3
      1523827.39      6764245.72      1523935.05      6764136.32
      1523999.18      6763912.73
#Sta/Elev= 30
  4848.9 2193.44  4852.7 2192.21  4866.8 2191.55  4888.0 2187.71  4902.1 2186.37
  4909.2 2184.31  4916.3 2184.05  4923.4 2181.80  4958.7 2178.20  4965.8 2176.19
  4980.0 2173.96  5009.0 2170.59  5009.3 2170.09  5013.0 2170.59  5018.3 2171.28
  5031.9 2176.80  5042.3 2178.88  5052.0 2179.67  5057.2 2179.06  5091.0 2182.79
  5096.2 2181.85  5124.7 2188.29  5129.9 2186.04  5135.9 2188.23  5156.7 2192.08
  5163.7 2194.19  5168.9 2191.75  5197.4 2197.54  5202.6 2194.82  5235.0 2198.94
#Mann=3,-1,0
  4848.9    0.16       0  5009.0    0.07       0  5013.0    0.16       0
Bank Sta=5009,5013
Exp/Cntr=0.3,0.1

Type RM Length L Ch R = 1,8188,88,88,88
BEGIN DESCRIPTION:
Elm 67 8187.59
END DESCRIPTION:
XS GIS Cut Line= 3
      1523891.61      6764257.86      1524032.27      6764221.39
      1524226.11      6764072.55
#Sta/Elev= 30
  4850.5 2186.31  4864.3 2185.04  4869.7 2182.91  4874.8 2184.01  4905.1 2178.11
  4910.3 2179.67  4916.0 2177.95  4945.7 2173.48  4950.9 2174.21  4967.6 2172.76
  4986.3 2169.55  4991.4 2170.17  4994.6 2169.52  5013.9 2169.13  5026.4 2167.54
  5026.6 2167.04  5030.1 2167.04  5030.4 2167.54  5042.9 2170.81  5057.4 2176.64
  5100.1 2179.93  5113.6 2181.64  5136.3 2182.69  5163.4 2185.92  5177.9 2185.75
  5200.7 2188.25  5207.0 2187.91  5221.5 2189.55  5227.8 2189.19  5240.2 2190.00
#Mann=3,-1,0
  4850.5    0.16       0  5026.4    0.07       0  5030.4    0.16       0
Bank Sta=5026.4,5030.4
Exp/Cntr=0.3,0.1

Type RM Length L Ch R = 1,8100,113,113,113
BEGIN DESCRIPTION:
Elm 67 8099.51
END DESCRIPTION:
XS GIS Cut Line= 3
      1523855.20      6764294.31      1524060.05      6764301.25
      1524251.36      6764271.96
#Sta/Elev= 30
  4799.5 2187.54  4819.3 2184.62  4839.3 2180.11  4859.3 2177.77  4879.3 2174.41
  4899.4 2172.39  4929.4 2171.28  4959.4 2170.98  4969.4 2169.87  4979.4 2166.36
  4987.4 2166.07  4987.7 2165.57  4991.2 2165.57  4991.4 2166.07  5004.4 2168.30
  5009.5 2168.30  5029.7 2170.28  5039.8 2172.28  5062.1 2174.47  5070.2 2175.86
  5100.5 2184.62  5110.6 2187.90  5120.4 2192.09  5125.4 2190.29  5130.9 2193.98
  5151.1 2200.12  5181.5 2205.34  5188.8 2206.40  5193.9 2205.73  5198.0 2207.03
#Mann=3,-1,0
  4799.5    0.16       0  4987.4    0.07       0  4991.4    0.16       0
Bank Sta=4987.4,4991.4
Exp/Cntr=0.3,0.1

Type RM Length L Ch R = 1,7987,81,81,81
BEGIN DESCRIPTION:
Elm 67 7987.411
END DESCRIPTION:
XS GIS Cut Line= 3
      1523755.01      6764338.00      1524000.86      6764393.35
      1524155.02      6764337.99
#Sta/Elev= 30
  4748.0 2196.76  4758.2 2196.31  4772.2 2193.86  4778.7 2191.21  4805.5 2188.40
  4815.5 2187.66  4820.6 2185.07  4840.2 2184.94  4850.5 2182.39  4871.0 2173.48
  4912.2 2169.50  4942.7 2168.65  4950.4 2167.85  4955.5 2165.62  4983.7 2167.24
  4998.8 2165.24  5046.9 2166.66  5076.8 2164.60  5077.0 2164.10  5080.8 2164.60
  5086.9 2169.59  5092.3 2169.52  5100.0 2174.96  5117.7 2183.11  5123.0 2181.27
  5142.5 2190.22  5148.4 2194.19  5153.7 2192.71  5161.1 2196.50  5163.8 2196.50
#Mann=4,-1,0
  4748.0    0.07       0  4805.5    0.16       0  5076.8    0.07       0
  5080.8    0.16       0
Bank Sta=5076.8,5080.8
Exp/Cntr=0.3,0.1

Type RM Length L Ch R = 1,7906,75,75,75
BEGIN DESCRIPTION:
Elm 67 7906.44
END DESCRIPTION:
XS GIS Cut Line= 3
      1523780.48      6764424.51      1523954.14      6764457.50
      1524188.56      6764445.35
#Sta/Elev= 30
  4822.4 2188.54  4837.2 2187.46  4851.3 2183.62  4865.3 2177.84  4870.3 2178.05
  4877.9 2174.54  4888.1 2172.36  4917.5 2168.73  4937.4 2167.26  4951.5 2166.57
  4959.3 2166.34  4969.5 2164.95  4974.8 2162.19  4987.9 2160.92  4988.1 2160.42
  4991.9 2160.92  4997.1 2162.56  5002.1 2162.56  5020.1 2165.08  5060.1 2168.74
  5080.1 2169.79  5085.7 2172.38  5090.7 2171.29  5100.2 2174.31  5140.2 2181.45
  5150.2 2185.28  5160.2 2187.48  5220.3 2191.49  5229.6 2193.91  5233.9 2193.91
#Mann=6,-1,0
  4822.4    0.07       0  4851.3    0.16       0  4937.4    0.07       0
  4951.5    0.16       0  4987.9    0.07       0  4991.9    0.16       0
Bank Sta=4987.9,4991.9
Exp/Cntr=0.3,0.1

Type RM Length L Ch R = 1,7831,78,78,78
BEGIN DESCRIPTION:
Elm 67 7831.17
END DESCRIPTION:
XS GIS Cut Line= 3
      1523756.25      6764476.61      1523917.69      6764521.74
      1524158.96      6764528.68
#Sta/Elev= 30
  4828.8 2175.50  4837.9 2173.13  4847.8 2175.12  4853.0 2171.62  4858.7 2174.81
  4869.0 2177.04  4879.4 2179.06  4891.1 2179.43  4900.2 2179.16  4921.0 2172.14
  4926.5 2168.99  4931.7 2170.50  4960.6 2165.00  4965.8 2164.68  4972.9 2162.74
  4983.6 2161.45  4996.4 2160.97  5001.7 2159.73  5002.0 2159.23  5005.7 2159.73
  5013.7 2160.39  5033.8 2165.26  5053.8 2165.71  5103.8 2168.58  5123.8 2171.61
  5143.8 2176.08  5153.8 2180.16  5183.8 2190.33  5213.8 2196.12  5237.8 2198.53
#Mann=5,-1,0
  4828.8    0.16       0  4891.1    0.07       0  4983.6    0.16       0
  5001.7    0.07       0  5005.7    0.16       0
Bank Sta=5001.7,5005.7
Exp/Cntr=0.3,0.1

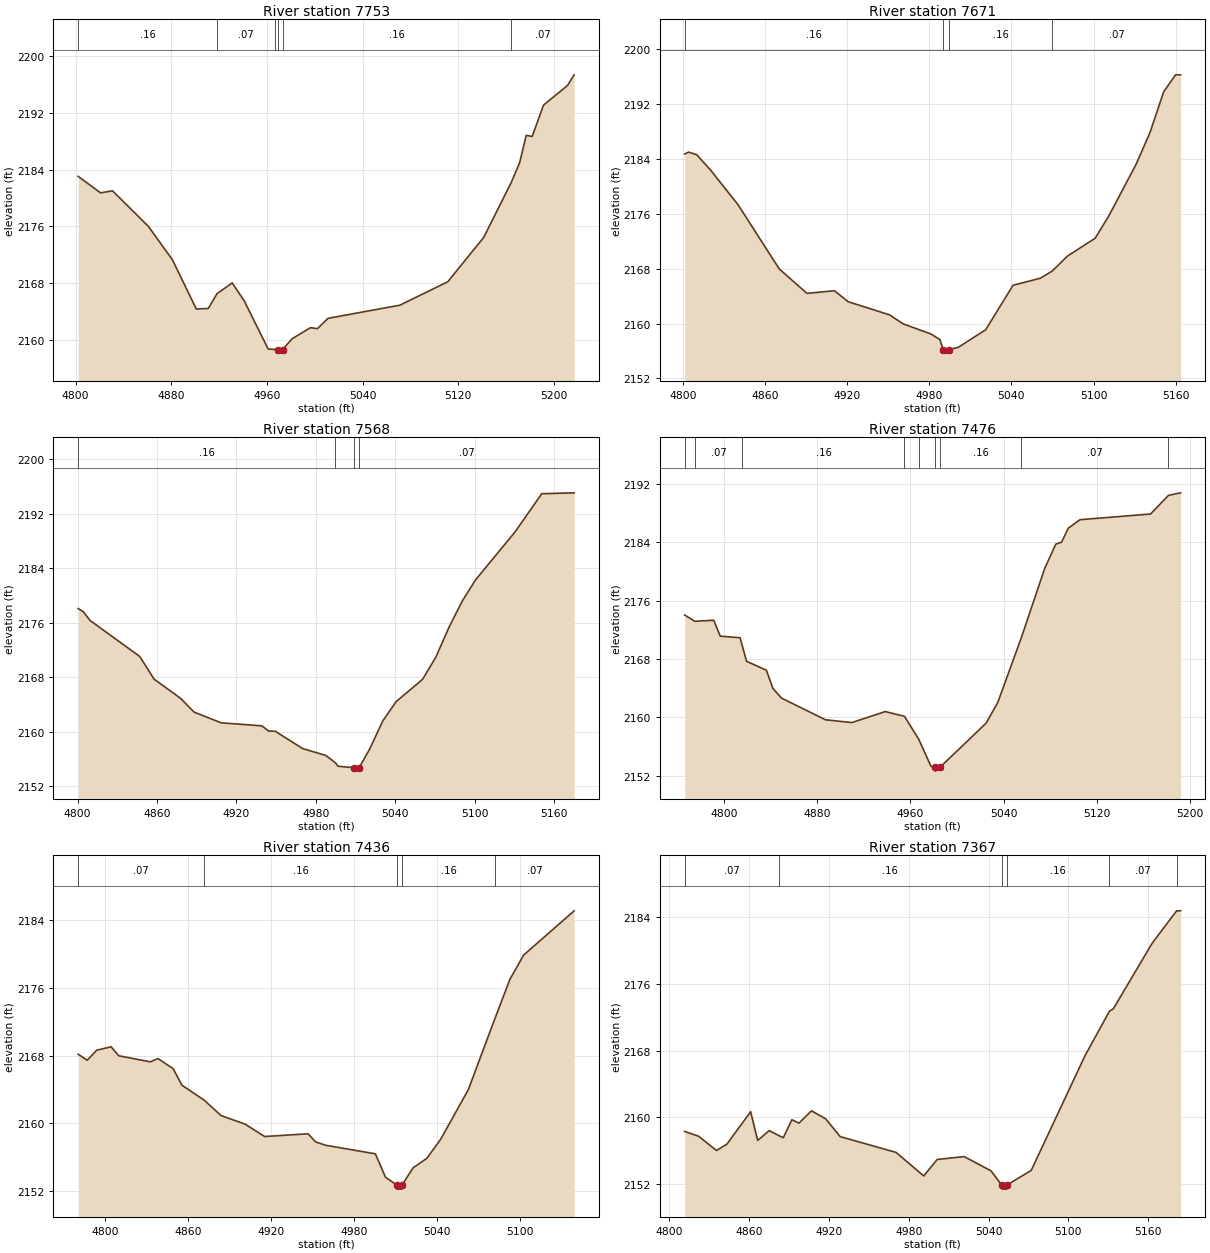
Type RM Length L Ch R = 1,7753,82,82,82
BEGIN DESCRIPTION:
Elm 67 7753.29
END DESCRIPTION:
XS GIS Cut Line= 3
      1523716.30      6764601.60      1523912.48      6764592.92
      1524130.57      6764580.81
#Sta/Elev= 30
  4802.2 2183.04  4820.9 2180.72  4830.9 2181.01  4861.0 2175.98  4881.0 2171.29
  4901.0 2164.36  4911.0 2164.44  4918.3 2166.52  4931.0 2168.04  4941.0 2165.53
  4961.1 2158.72  4966.4 2158.67  4969.1 2158.65  4969.3 2158.15  4972.8 2158.15
  4973.1 2158.65  4981.1 2160.17  4996.4 2161.73  5002.3 2161.60  5011.1 2163.05
  5071.2 2164.90  5111.3 2168.20  5141.3 2174.43  5164.4 2182.19  5171.4 2184.96
  5176.9 2188.81  5181.9 2188.66  5191.4 2193.08  5211.4 2195.83  5217.0 2197.34
#Mann=6,-1,0
  4802.2    0.16       0  4918.3    0.07       0  4966.4    0.16       0
  4969.1    0.07       0  4973.1    0.16       0  5164.4    0.07       0
Bank Sta=4969.1,4973.1
Exp/Cntr=0.3,0.1

Type RM Length L Ch R = 1,7671,103,103,103
BEGIN DESCRIPTION:
Elm 67 7670.51
END DESCRIPTION:
XS GIS Cut Line= 3
      1523756.25      6764683.20      1523948.94      6764662.37
      1524117.35      6764657.16
#Sta/Elev= 30
  4801.3 2184.74  4804.1 2185.02  4810.1 2184.64  4820.2 2182.40  4840.3 2177.34
  4870.4 2167.98  4890.6 2164.42  4910.7 2164.80  4920.7 2163.20  4950.9 2161.29
  4961.0 2159.96  4981.1 2158.50  4987.7 2157.69  4990.2 2156.20  4990.4 2155.70
  4993.9 2155.70  4994.2 2156.20  5001.2 2156.55  5021.2 2159.11  5041.2 2165.60
  5061.2 2166.63  5069.7 2167.66  5081.2 2169.89  5101.2 2172.46  5111.2 2175.73
  5131.2 2183.29  5141.2 2187.86  5151.2 2193.80  5159.9 2196.29  5163.6 2196.29
#Mann=4,-1,0
  4801.3    0.16       0  4990.2    0.07       0  4994.2    0.16       0
  5069.7    0.07       0
Bank Sta=4990.2,4994.2
Exp/Cntr=0.3,0.1

Type RM Length L Ch R = 1,7568,92,92,92
BEGIN DESCRIPTION:
Elm 67 7567.89
END DESCRIPTION:
XS GIS Cut Line= 3
      1523759.66      6764721.38      1523952.41      6764764.80
      1524129.50      6764768.27
#Sta/Elev= 30
  4800.5 2178.05  4804.3 2177.59  4809.5 2176.30  4847.0 2171.02  4857.9 2167.68
  4877.7 2164.90  4888.0 2162.86  4908.5 2161.28  4939.2 2160.84  4944.4 2160.07
  4949.5 2160.03  4970.0 2157.51  4987.6 2156.49  4994.7 2155.44  4996.8 2154.91
  5008.7 2154.69  5008.9 2154.19  5012.4 2154.19  5012.7 2154.69  5020.7 2157.42
  5030.7 2161.59  5040.7 2164.39  5060.7 2167.67  5070.7 2170.92  5080.7 2175.33
  5090.7 2179.16  5100.7 2182.26  5130.7 2189.34  5150.7 2194.91  5175.2 2195.04
#Mann=4,-1,0
  4800.5    0.16       0  4994.7    0.07       0  5008.7    0.07       0
  5012.7    0.07       0
Bank Sta=5008.7,5012.7
Exp/Cntr=0.3,0.1

Type RM Length L Ch R = 1,7476,40,40,40
BEGIN DESCRIPTION:
Elm 67 7476.32
END DESCRIPTION:
XS GIS Cut Line= 3
      1523730.17      6764750.90      1523941.99      6764853.34
      1524130.66      6764830.84
#Sta/Elev= 30
  4766.5 2174.02  4775.2 2173.15  4791.4 2173.30  4797.0 2171.12  4814.0 2170.90
  4815.9 2169.80  4819.6 2167.67  4836.6 2166.45  4842.2 2163.94  4849.6 2162.63
  4887.3 2159.66  4909.9 2159.28  4938.5 2160.79  4955.0 2160.14  4967.2 2157.01
  4977.7 2153.30  4981.3 2153.13  4981.5 2152.63  4985.3 2153.13  5025.0 2159.20
  5035.0 2162.03  5055.2 2170.91  5075.3 2180.41  5084.7 2183.71  5089.8 2184.01
  5095.5 2185.91  5105.5 2187.07  5166.0 2187.85  5181.4 2190.40  5191.8 2190.75
#Mann=9,-1,0
  4766.5    0.16       0  4775.2    0.07       0  4815.9    0.16       0
  4955.0    0.07       0  4967.2    0.16       0  4981.3    0.07       0
  4985.3    0.16       0  5055.2    0.07       0  5181.4   0.035       0
Bank Sta=4981.3,4985.3
Exp/Cntr=0.3,0.1

Type RM Length L Ch R = 1,7436,69,69,69
BEGIN DESCRIPTION:
Elm 67 7436.36
END DESCRIPTION:
XS GIS Cut Line= 3
      1523712.83      6764790.84      1523905.53      6764881.12
      1524051.53      6764881.12
#Sta/Elev= 30
  4780.3 2168.15  4786.8 2167.44  4793.7 2168.63  4804.1 2169.03  4809.6 2167.97
  4832.5 2167.25  4838.0 2167.64  4849.0 2166.44  4855.3 2164.49  4871.5 2162.71
  4883.6 2160.89  4901.0 2159.88  4915.2 2158.41  4946.6 2158.73  4952.1 2157.77
  4959.4 2157.37  4995.3 2156.36  5002.6 2153.60  5010.6 2152.68  5010.8 2152.18
  5014.3 2152.18  5014.6 2152.68  5022.6 2154.70  5032.6 2155.84  5042.6 2158.10
  5062.6 2163.98  5081.7 2172.34  5092.6 2177.01  5102.6 2179.90  5139.1 2185.13
#Mann=5,-1,0
  4780.3    0.07       0  4871.5    0.16       0  5010.6    0.07       0
  5014.6    0.16       0  5081.7    0.07       0
Bank Sta=5010.6,5014.6
Exp/Cntr=0.3,0.1

Type RM Length L Ch R = 1,7367,105,105,105
BEGIN DESCRIPTION:
Elm 67 7366.5
END DESCRIPTION:
XS GIS Cut Line= 3
      1523685.08      6764875.92      1523848.24      6764933.20
      1524046.18      6764905.42
#Sta/Elev= 30
  4811.6 2158.31  4822.1 2157.73  4835.5 2156.03  4843.3 2156.78  4861.2 2160.67
  4866.5 2157.23  4875.1 2158.41  4882.5 2157.81  4885.7 2157.55  4892.2 2159.71
  4897.5 2159.30  4906.9 2160.78  4917.5 2159.83  4928.5 2157.69  4970.5 2155.80
  4991.3 2152.98  5001.4 2154.95  5021.6 2155.30  5041.8 2153.60  5049.9 2151.90
  5050.2 2151.40  5053.7 2151.40  5053.9 2151.90  5072.1 2153.64  5112.5 2167.37
  5130.9 2172.71  5133.8 2172.99  5163.0 2180.85  5181.4 2184.73  5184.4 2184.73
#Mann=6,-1,0
  4811.6    0.07       0  4882.5    0.16       0  5049.9    0.07       0
  5053.9    0.16       0  5130.9    0.07       0  5181.4   0.035       0
Bank Sta=5049.9,5053.9
Exp/Cntr=0.3,0.1

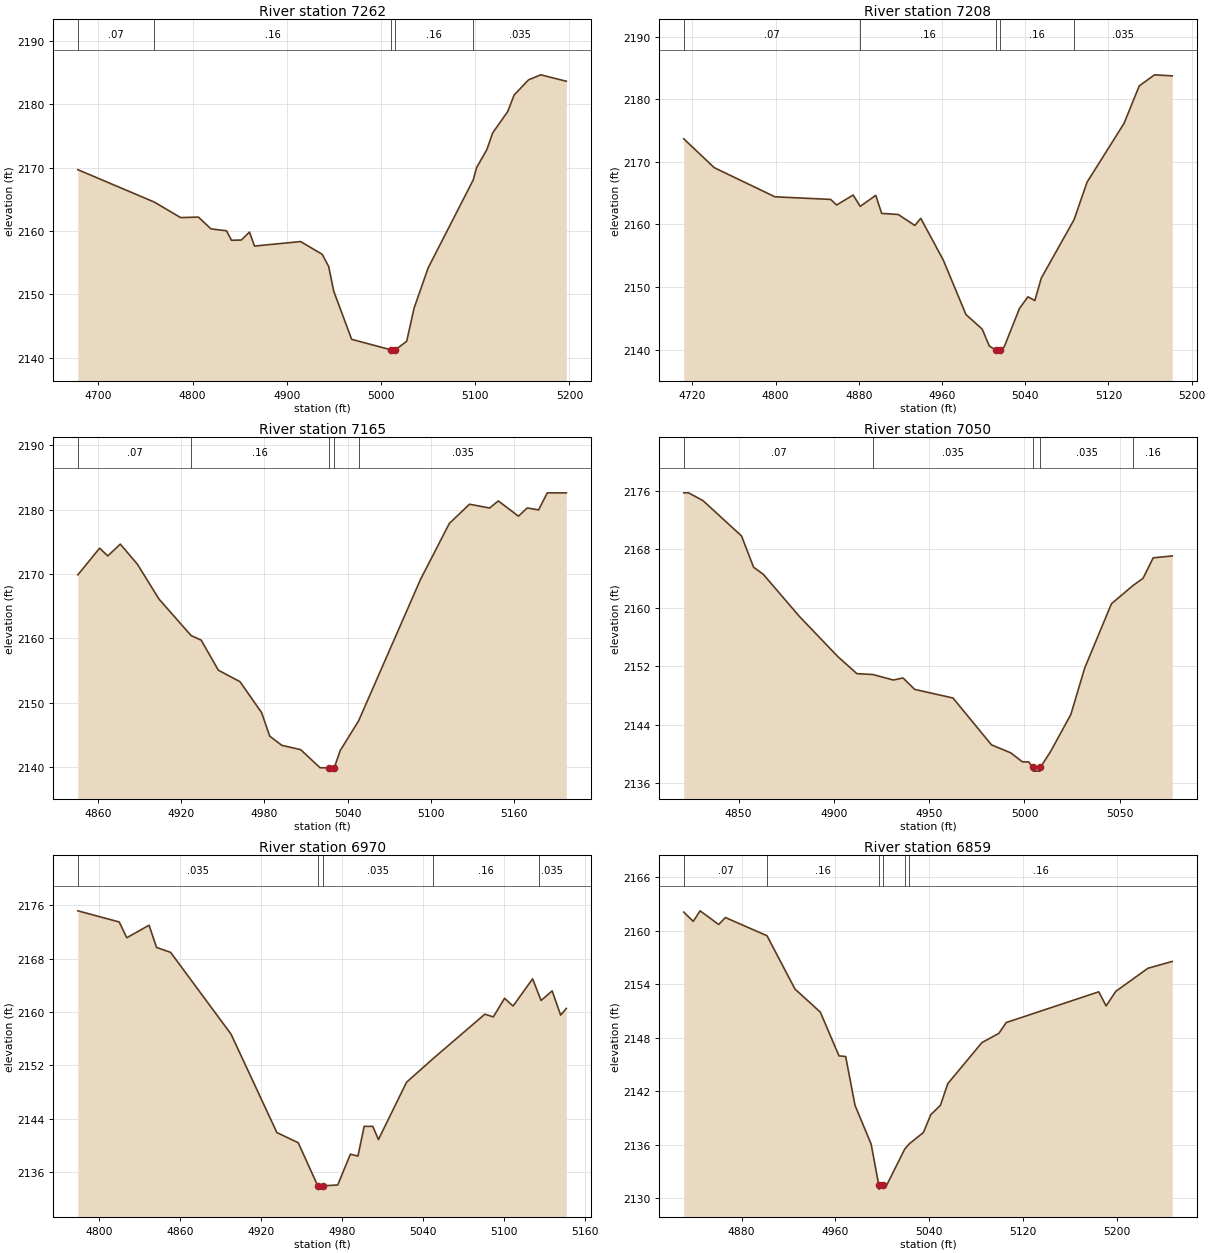
Type RM Length L Ch R = 1,7262,54,54,54
BEGIN DESCRIPTION:
Elm 67 7261.72
END DESCRIPTION:
XS GIS Cut Line= 3
      1523603.41      6765120.72      1523909.01      6765000.91
      1524081.28      6764919.94
#Sta/Elev= 30
  4678.1 2169.69  4759.4 2164.57  4787.2 2162.13  4806.1 2162.21  4819.4 2160.35
  4835.9 2160.05  4841.3 2158.55  4851.7 2158.59  4860.3 2159.85  4865.7 2157.64
  4914.6 2158.35  4937.6 2156.33  4944.4 2154.41  4949.8 2150.51  4968.8 2142.93
  5011.0 2141.25  5011.2 2140.75  5015.0 2141.25  5027.2 2142.61  5035.1 2147.85
  5050.0 2154.19  5097.9 2168.08  5101.4 2170.01  5112.4 2172.87  5118.5 2175.48
  5134.5 2178.86  5141.3 2181.47  5156.6 2183.86  5169.6 2184.65  5196.7 2183.64
#Mann=5,-1,0
  4678.1    0.07       0  4759.4    0.16       0  5011.0    0.07       0
  5015.0    0.16       0  5097.9   0.035       0
Bank Sta=5011,5015
Exp/Cntr=0.3,0.1

Type RM Length L Ch R = 1,7208,43,43,43
BEGIN DESCRIPTION:
Elm 67 7208.42
END DESCRIPTION:
XS GIS Cut Line= 3
      1523669.45      6765193.60      1523919.42      6765052.99
      1524067.02      6764945.33
#Sta/Elev= 30
  4711.8 2173.67  4741.1 2169.06  4799.4 2164.41  4853.0 2163.99  4858.7 2163.10
  4874.6 2164.69  4881.4 2162.88  4896.3 2164.64  4902.0 2161.76  4918.0 2161.58
  4933.9 2159.83  4939.6 2160.97  4961.3 2154.28  4983.0 2145.61  4998.6 2143.28
  5005.5 2140.57  5011.6 2139.94  5011.9 2139.44  5015.6 2139.94  5019.8 2140.45
  5034.5 2146.59  5042.6 2148.44  5049.2 2147.84  5055.4 2151.42  5086.9 2160.75
  5099.4 2166.74  5134.9 2176.12  5149.6 2182.13  5164.3 2183.89  5181.3 2183.72
#Mann=5,-1,0
  4711.8    0.07       0  4881.4    0.16       0  5011.6    0.07       0
  5015.6    0.16       0  5086.9   0.035       0
Bank Sta=5011.6,5015.6
Exp/Cntr=0.3,0.1

Type RM Length L Ch R = 1,7165,115,115,115
BEGIN DESCRIPTION:
Elm 67 7164.75
END DESCRIPTION:
XS GIS Cut Line= 3
      1523818.70      6765162.38      1523952.41      6765082.50
      1524107.39      6764961.96
#Sta/Elev= 30
  4845.5 2169.88  4861.2 2174.03  4867.1 2172.83  4876.1 2174.66  4888.5 2171.52
  4904.0 2166.12  4927.2 2160.44  4934.4 2159.74  4946.8 2155.06  4962.4 2153.28
  4978.0 2148.46  4983.8 2144.82  4992.6 2143.38  5006.1 2142.72  5020.1 2139.91
  5026.3 2139.88  5026.5 2139.38  5030.3 2139.88  5034.6 2142.57  5047.9 2147.20
  5092.5 2169.17  5113.3 2177.88  5127.8 2180.86  5142.3 2180.27  5148.6 2181.37
  5163.1 2179.00  5169.4 2180.28  5177.6 2179.97  5183.9 2182.63  5197.6 2182.62
#Mann=5,-1,0
  4845.5    0.07       0  4927.2    0.16       0  5026.3    0.07       0
  5030.3    0.16       0  5047.9   0.035       0
Bank Sta=5026.3,5030.3
Exp/Cntr=0.3,0.1

Type RM Length L Ch R = 1,7050,80,80,80
BEGIN DESCRIPTION:
Elm 67 7050.109
END DESCRIPTION:
XS GIS Cut Line= 3
      1523854.99      6765188.00      1524032.14      6765164.47
      1524104.98      6765138.01
#Sta/Elev= 30
  4821.3 2175.71  4823.8 2175.71  4831.4 2174.64  4851.6 2169.81  4857.9 2165.54
  4863.0 2164.57  4881.8 2158.85  4902.0 2153.34  4912.1 2150.98  4920.5 2150.86
  4931.2 2150.11  4936.3 2150.39  4942.4 2148.83  4962.5 2147.65  4982.7 2141.24
  4992.8 2140.15  4998.9 2138.92  5002.2 2138.92  5004.3 2138.15  5004.6 2137.65
  5008.1 2137.65  5008.3 2138.15  5013.7 2140.34  5024.3 2145.39  5031.6 2151.76
  5045.6 2160.54  5056.9 2163.03  5062.2 2164.03  5067.5 2166.82  5077.5 2167.08
#Mann=5,-1,0
  4821.3    0.07       0  4920.5   0.035       0  5004.3   0.035       0
  5008.3   0.035       0  5056.9    0.16       0
Bank Sta=5004.3,5008.3
Exp/Cntr=0.3,0.1

Type RM Length L Ch R = 1,6970,111,111,111
BEGIN DESCRIPTION:
Elm 67 6969.58
END DESCRIPTION:
XS GIS Cut Line= 3
      1523863.91      6765337.69      1524054.84      6765238.75
      1524144.23      6765121.86
#Sta/Elev= 30
  4784.2 2175.14  4814.9 2173.47  4820.5 2171.11  4837.0 2172.98  4842.6 2169.65
  4853.0 2168.92  4897.8 2156.67  4931.8 2141.93  4947.6 2140.41  4962.1 2133.96
  4962.4 2133.46  4966.1 2133.96  4976.9 2134.08  4986.3 2138.69  4991.9 2138.41
  4996.5 2142.86  5002.9 2142.86  5007.1 2140.89  5027.9 2149.46  5047.4 2152.97
  5086.0 2159.66  5092.3 2159.25  5100.6 2162.04  5106.9 2160.88  5121.4 2164.95
  5125.8 2162.69  5127.7 2161.71  5135.9 2163.15  5142.2 2159.52  5146.4 2160.52
#Mann=5,-1,0
  4784.2   0.035       0  4962.1   0.035       0  4966.1   0.035       0
  5047.4    0.16       0  5125.8   0.035       0
Bank Sta=4962.1,4966.1
Exp/Cntr=0.3,0.1

Type RM Length L Ch R = 1,6859,108,108,108
BEGIN DESCRIPTION:
Elm 67 6858.73
END DESCRIPTION:
XS GIS Cut Line= 3
      1523917.72      6765429.71      1524068.73      6765344.66
      1524216.96      6765151.61
#Sta/Elev= 30
  4830.7 2162.07  4838.8 2161.03  4844.6 2162.21  4860.5 2160.68  4866.2 2161.46
  4901.7 2159.42  4925.5 2153.46  4947.2 2150.86  4963.1 2145.97  4968.8 2145.89
  4976.8 2140.42  4990.5 2136.10  4997.0 2131.54  4997.3 2131.04  5001.0 2131.54
  5004.0 2131.54  5019.2 2135.53  5023.2 2136.13  5035.1 2137.38  5041.4 2139.38
  5049.6 2140.42  5055.9 2142.85  5085.0 2147.45  5099.5 2148.49  5105.8 2149.70
  5184.7 2153.14  5191.0 2151.56  5199.2 2153.19  5226.7 2155.78  5247.4 2156.54
#Mann=6,-1,0
  4830.7    0.07       0  4901.7    0.16       0  4997.0    0.07       0
  5001.0    0.16       0  5019.2   0.035       0  5023.2    0.16       0
Bank Sta=4997,5001
Exp/Cntr=0.3,0.1

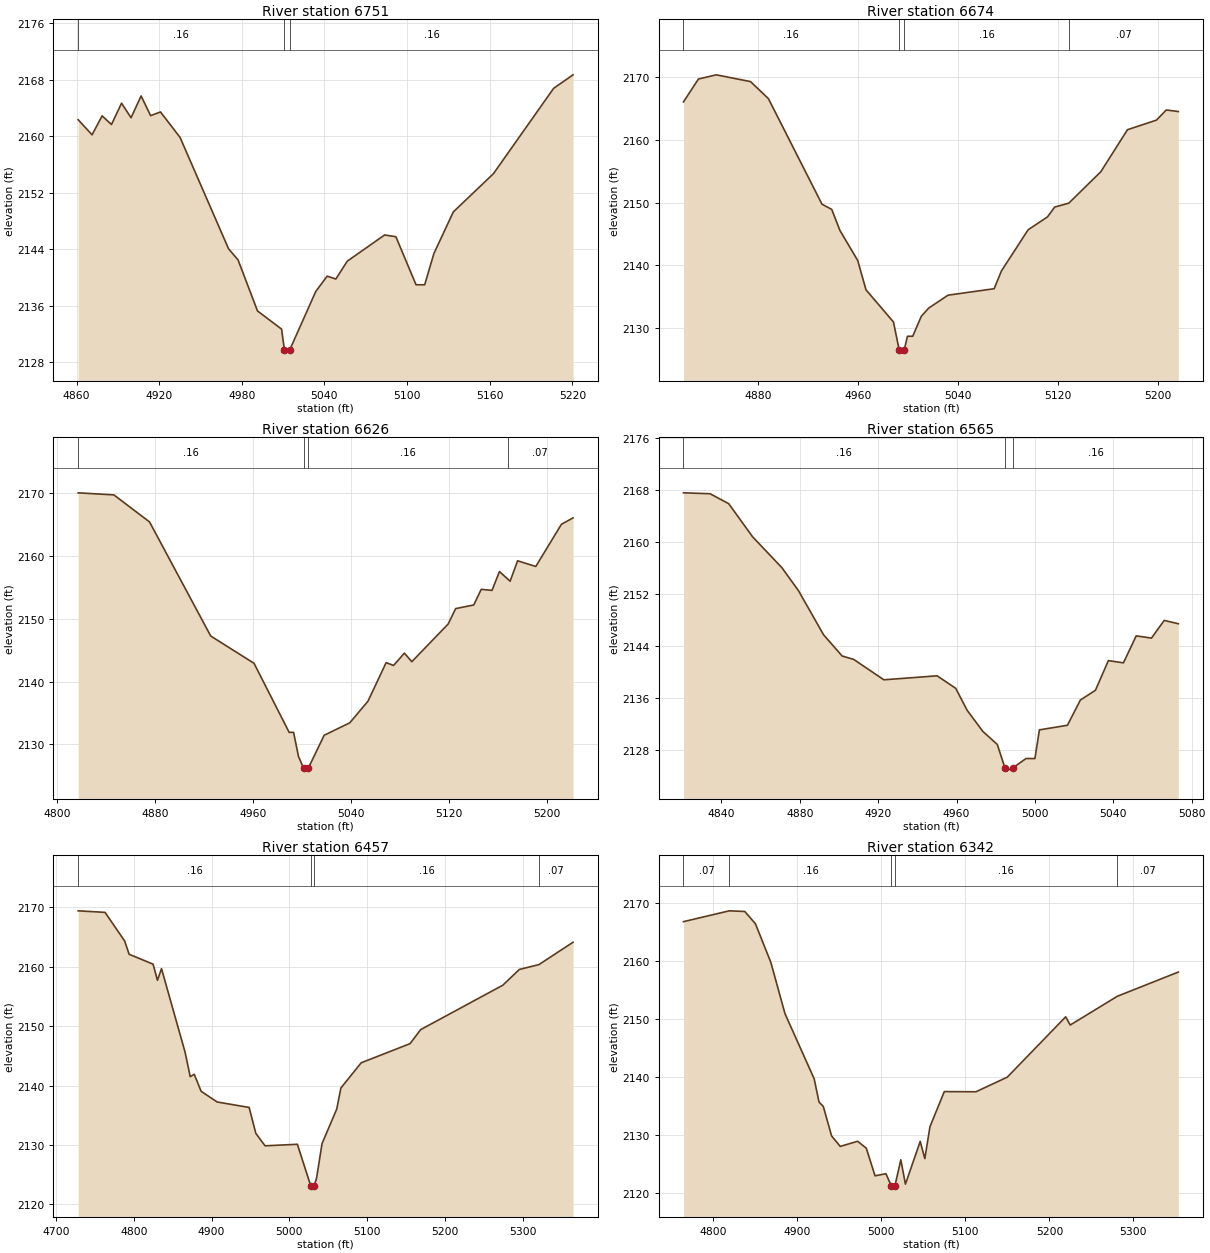
Type RM Length L Ch R = 1,6751,77,77,77
BEGIN DESCRIPTION:
Elm 67 6750.86
END DESCRIPTION:
XS GIS Cut Line= 3
      1524040.93      6765518.29      1524145.12      6765419.31
      1524275.31      6765247.46
#Sta/Elev= 30
  4861.2 2162.34  4871.3 2160.20  4878.6 2162.89  4885.4 2161.66  4892.7 2164.68
  4899.6 2162.62  4906.9 2165.71  4913.8 2162.92  4921.0 2163.44  4935.2 2159.83
  4970.4 2144.05  4977.3 2142.48  4991.4 2135.25  5008.9 2132.67  5010.9 2129.77
  5011.2 2129.27  5014.9 2129.77  5033.7 2138.00  5042.0 2140.18  5048.3 2139.77
  5056.6 2142.30  5083.7 2146.01  5091.9 2145.76  5106.5 2138.96  5112.8 2138.95
  5119.5 2143.39  5133.6 2149.28  5162.7 2154.69  5206.4 2166.78  5220.5 2168.70
#Mann=3,-1,0
  4861.2    0.16       0  5010.9    0.07       0  5014.9    0.16       0
Bank Sta=5010.9,5014.9
Exp/Cntr=0.3,0.1

Type RM Length L Ch R = 1,6674,48,48,48
BEGIN DESCRIPTION:
Elm 67 6674.24
END DESCRIPTION:
XS GIS Cut Line= 3
      1524073.97      6765563.38      1524212.82      6765447.09
      1524323.94      6765263.05
#Sta/Elev= 30
  4820.1 2166.08  4832.1 2169.74  4846.4 2170.41  4873.8 2169.33  4888.1 2166.61
  4931.0 2149.76  4938.8 2148.93  4945.3 2145.59  4959.6 2140.77  4966.2 2136.10
  4988.2 2130.96  4992.8 2126.49  4993.0 2125.99  4996.8 2126.49  4999.4 2128.68
  5003.6 2128.68  5010.5 2131.87  5016.4 2133.18  5031.9 2135.24  5068.8 2136.27
  5074.6 2139.10  5096.0 2145.68  5111.5 2147.74  5117.3 2149.31  5128.5 2149.92
  5154.2 2154.95  5175.5 2161.65  5198.7 2163.18  5206.6 2164.80  5216.2 2164.55
#Mann=4,-1,0
  4820.1    0.16       0  4992.8    0.07       0  4996.8    0.16       0
  5128.5    0.07       0
Bank Sta=4992.8,4996.8
Exp/Cntr=0.3,0.1

Type RM Length L Ch R = 1,6626,61,61,61
BEGIN DESCRIPTION:
Elm 67 6625.92
END DESCRIPTION:
XS GIS Cut Line= 3
      1524105.19      6765589.44      1524245.81      6765483.55
      1524376.01      6765296.05
#Sta/Elev= 30
  4817.3 2170.04  4846.5 2169.71  4875.6 2165.41  4925.6 2147.25  4961.0 2142.90
  4989.7 2131.91  4993.3 2131.91  4997.3 2128.09  5001.4 2126.24  5001.7 2125.74
  5005.4 2126.24  5018.3 2131.45  5039.2 2133.43  5054.1 2136.88  5068.9 2143.01
  5075.0 2142.56  5083.8 2144.52  5089.9 2143.16  5119.6 2149.16  5125.7 2151.61
  5140.5 2152.19  5146.6 2154.68  5155.4 2154.51  5161.5 2157.51  5168.1 2156.34
  5170.2 2155.97  5176.3 2159.22  5191.2 2158.32  5212.1 2165.03  5221.6 2166.05
#Mann=4,-1,0
  4817.3    0.16       0  5001.4    0.07       0  5005.4    0.16       0
  5168.1    0.07       0
Bank Sta=5001.4,5005.4
Exp/Cntr=0.3,0.1

Type RM Length L Ch R = 1,6565,108,108,108
BEGIN DESCRIPTION:
Elm 67 6564.974
END DESCRIPTION:
XS GIS Cut Line= 3
      1524154.97      6765588.02      1524307.59      6765493.72
      1524355.03      6765437.97
#Sta/Elev= 30
  4820.6 2167.60  4834.2 2167.46  4843.7 2165.93  4855.9 2160.83  4870.9 2156.06
  4879.4 2152.50  4892.1 2145.76  4901.6 2142.48  4907.5 2141.96  4922.9 2138.82
  4950.1 2139.43  4959.6 2137.50  4965.4 2134.13  4973.4 2130.88  4980.8 2128.87
  4984.7 2125.26  4985.0 2124.76  4988.7 2125.26  4995.5 2126.70  5000.0 2126.70
  5002.3 2131.11  5016.6 2131.82  5023.2 2135.70  5030.9 2137.21  5037.5 2141.77
  5045.2 2141.43  5051.7 2145.58  5059.5 2145.24  5066.0 2147.96  5073.2 2147.45
#Mann=3,-1,0
  4820.6    0.16       0  4984.7    0.07       0  4988.7    0.16       0
Bank Sta=4984.7,4988.7
Exp/Cntr=0.3,0.1

Type RM Length L Ch R = 1,6457,115,115,115
BEGIN DESCRIPTION:
Elm 67 6456.56
END DESCRIPTION:
XS GIS Cut Line= 3
      1524091.30      6765646.74      1524353.45      6765584.24
      1524700.35      6765466.29
#Sta/Elev= 30
  4728.6 2169.43  4763.2 2169.17  4788.4 2164.34  4794.1 2162.12  4824.9 2160.45
  4830.5 2157.73  4835.7 2159.70  4866.0 2145.64  4872.6 2141.51  4877.8 2141.91
  4886.6 2139.05  4907.2 2137.25  4948.3 2136.33  4956.9 2131.97  4968.8 2129.87
  5010.3 2130.13  5027.6 2123.08  5027.8 2122.58  5031.6 2123.08  5034.9 2124.39
  5042.0 2130.25  5060.9 2136.07  5066.2 2139.60  5092.3 2143.85  5155.1 2147.07
  5168.7 2149.43  5274.3 2156.91  5295.5 2159.56  5320.6 2160.37  5364.5 2164.14
#Mann=4,-1,0
  4728.6    0.16       0  5027.6    0.07       0  5031.6    0.16       0
  5320.6    0.07       0
Bank Sta=5027.6,5031.6
Exp/Cntr=0.3,0.1

Type RM Length L Ch R = 1,6342,120,120,120
BEGIN DESCRIPTION:
Elm 67 6341.8
END DESCRIPTION:
XS GIS Cut Line= 3
      1524084.36      6765743.96      1524310.05      6765684.94
      1524634.72      6765539.09
#Sta/Elev= 30
  4764.3 2166.85  4818.9 2168.72  4837.3 2168.61  4850.0 2166.49  4868.3 2159.84
  4885.2 2150.95  4920.0 2139.68  4925.7 2135.69  4930.8 2134.93  4940.7 2129.83
  4951.0 2128.02  4971.7 2128.91  4982.0 2127.71  4992.4 2122.94  5005.4 2123.30
  5012.0 2121.14  5012.2 2120.64  5016.0 2121.14  5023.1 2125.71  5028.6 2121.50
  5046.2 2128.88  5051.7 2125.91  5057.8 2131.42  5074.9 2137.49  5112.6 2137.46
  5149.9 2139.99  5219.4 2150.41  5224.8 2148.99  5280.9 2153.96  5353.5 2158.14
#Mann=5,-1,0
  4764.3    0.07       0  4818.9    0.16       0  5012.0    0.07       0
  5016.0    0.16       0  5280.9    0.07       0
Bank Sta=5012,5016
Exp/Cntr=0.3,0.1