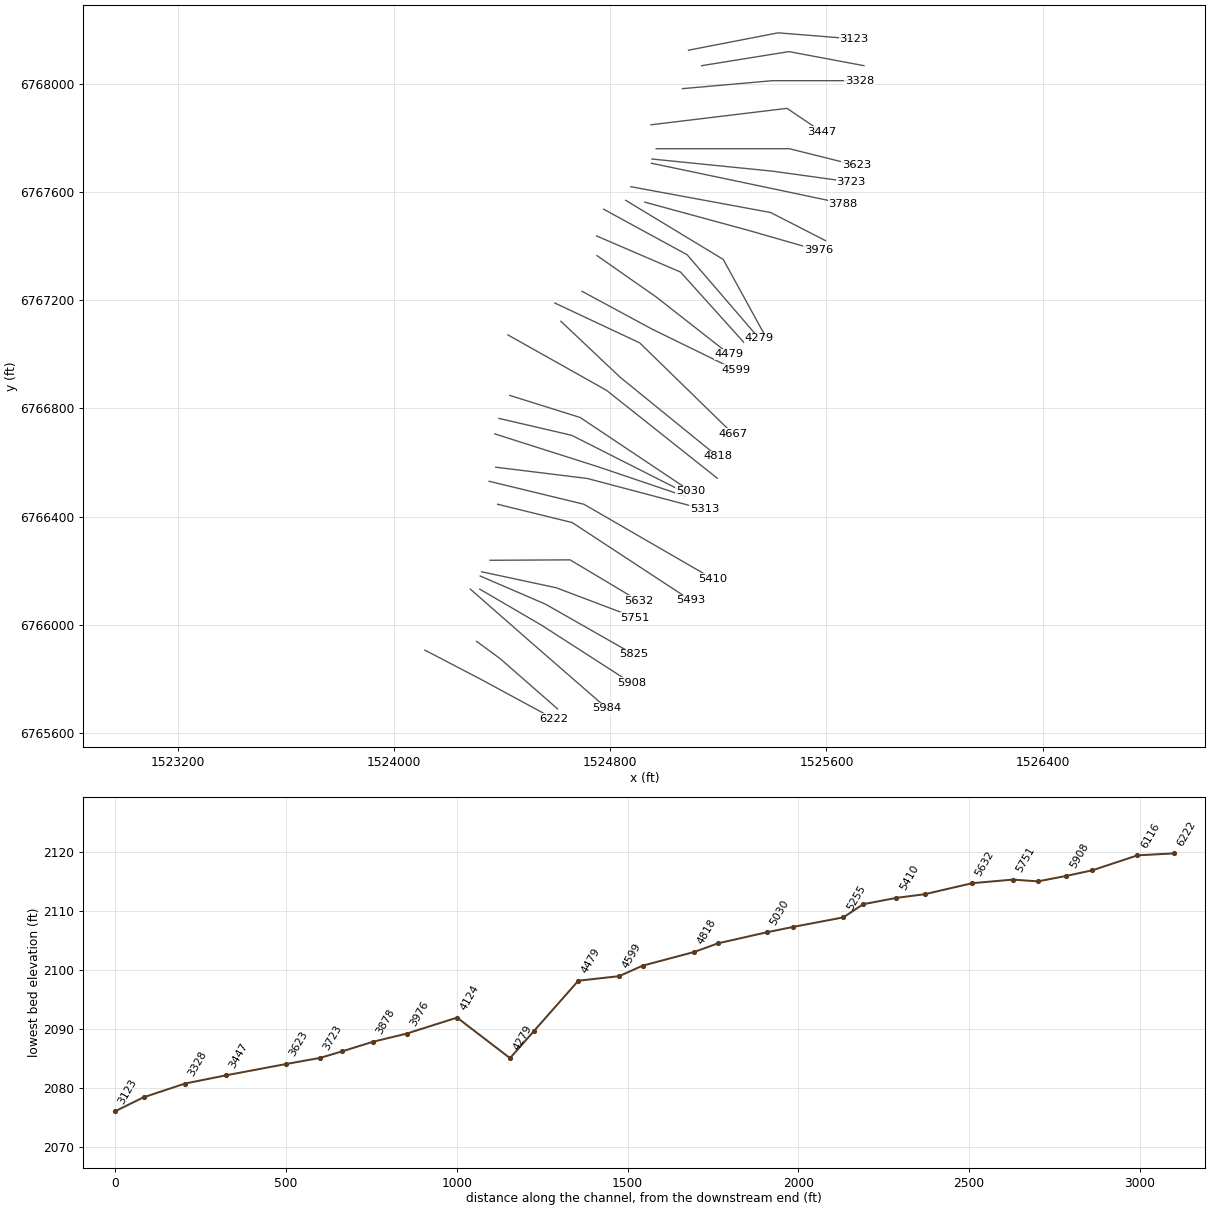
HEC-RAS study Elm 67.prj: Elm 67 Base Level Engineering

--- Elm 67.g01 (geometry) --- (continued)

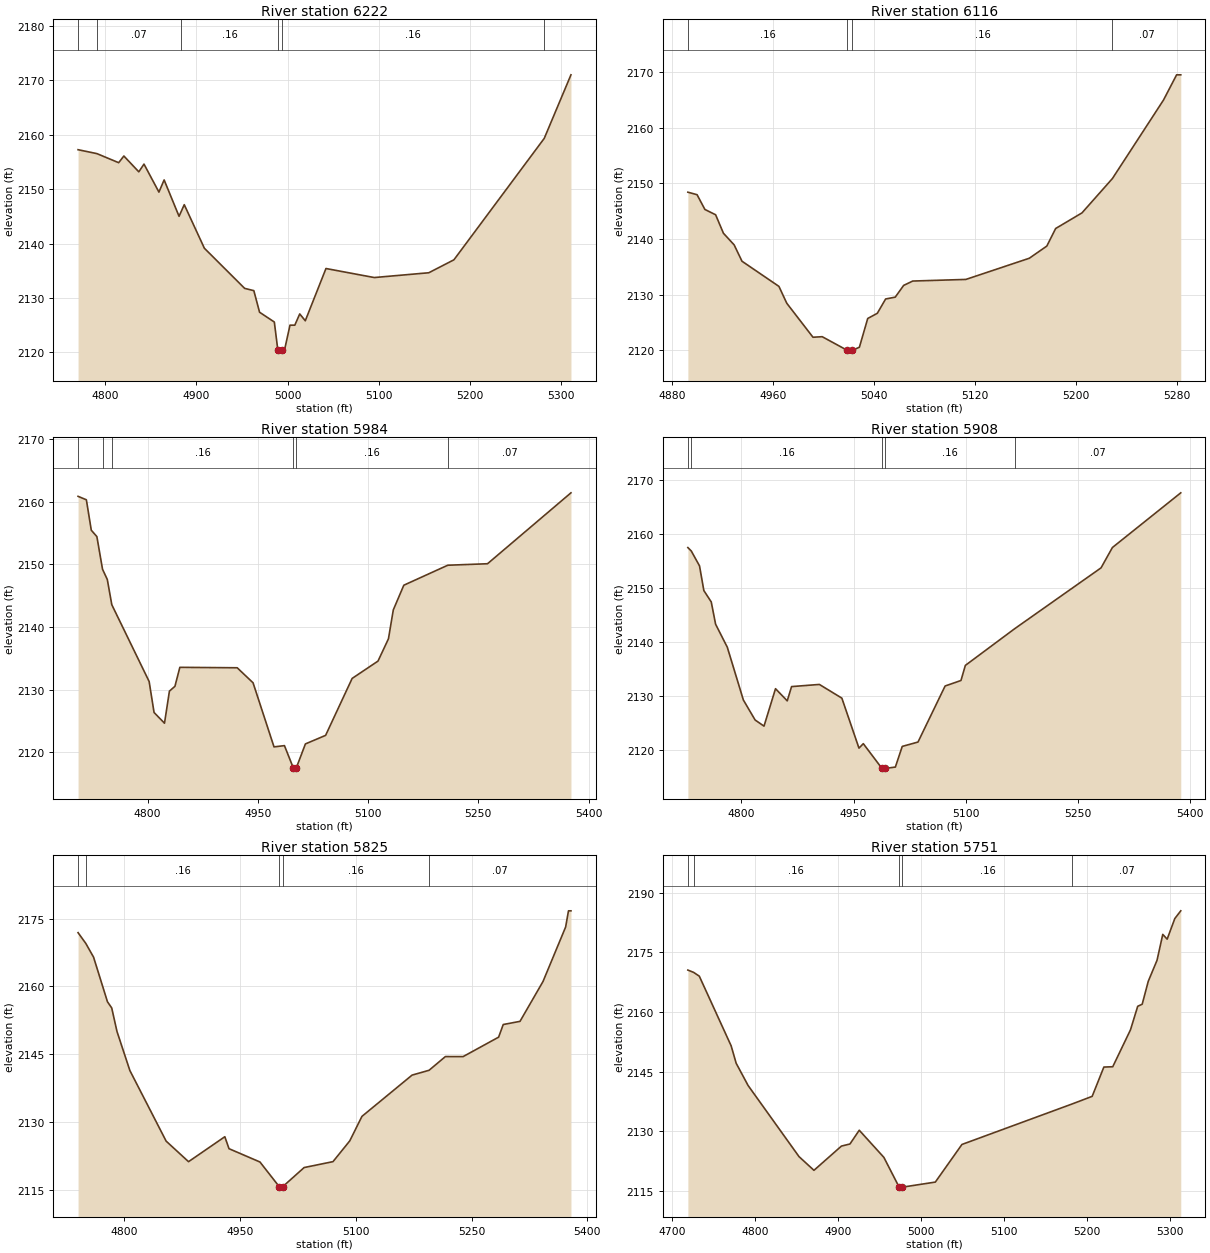
Type RM Length L Ch R = 1,6222,106,106,106
BEGIN DESCRIPTION:
Elm 67 6221.92
END DESCRIPTION:
XS GIS Cut Line= 3
      1524113.87      6765905.42      1524320.46      6765797.78
      1524591.53      6765651.03
#Sta/Elev= 30
  4770.0 2157.25  4790.7 2156.53  4814.6 2154.86  4820.3 2156.09  4836.7 2153.18
  4842.4 2154.60  4858.8 2149.45  4864.5 2151.69  4880.9 2145.00  4883.4 2145.94
  4886.6 2147.14  4908.7 2139.13  4952.9 2131.75  4963.0 2131.33  4969.3 2127.36
  4985.5 2125.56  4989.4 2120.34  4989.7 2119.84  4993.4 2120.34  4997.0 2120.64
  5002.7 2124.98  5008.0 2124.98  5013.4 2127.05  5019.5 2125.79  5042.2 2135.40
  5095.2 2133.74  5155.1 2134.62  5182.7 2137.00  5281.9 2159.34  5311.2 2171.02
#Mann=6,-1,0
  4770.0    0.16       0  4790.7    0.07       0  4883.4    0.16       0
  4989.4    0.07       0  4993.4    0.16       0  5281.9    0.07       0
Bank Sta=4989.4,4993.4
Exp/Cntr=0.3,0.1

Type RM Length L Ch R = 1,6116,132,132,132
BEGIN DESCRIPTION:
Elm 67 6116.328
END DESCRIPTION:
XS GIS Cut Line= 3
      1524304.99      6765938.01      1524391.76      6765874.38
      1524604.99      6765688.01
#Sta/Elev= 30
  4892.4 2148.40  4899.7 2147.95  4905.9 2145.30  4914.4 2144.35  4920.6 2141.03
  4929.1 2138.94  4935.3 2136.01  4964.6 2131.49  4970.8 2128.47  4991.6 2122.36
  4998.9 2122.46  5018.8 2120.01  5019.0 2119.51  5022.8 2120.01  5028.4 2120.57
  5035.0 2125.73  5042.6 2126.66  5049.2 2129.23  5056.8 2129.56  5063.5 2131.67
  5070.7 2132.45  5112.8 2132.74  5163.1 2136.54  5177.0 2138.73  5184.0 2141.88
  5204.9 2144.69  5229.0 2150.85  5269.5 2164.94  5279.9 2169.47  5283.2 2169.47
#Mann=4,-1,0
  4892.4    0.16       0  5018.8    0.07       0  5022.8    0.16       0
  5229.0    0.07       0
Bank Sta=5018.8,5022.8
Exp/Cntr=0.3,0.1

Type RM Length L Ch R = 1,5984,76,76,76
BEGIN DESCRIPTION:
Elm 67 5983.56
END DESCRIPTION:
XS GIS Cut Line= 3
      1524282.25      6766131.13      1524507.96      6765933.20
      1524787.46      6765690.15
#Sta/Elev= 30
  4705.5 2160.85  4716.8 2160.30  4723.5 2155.44  4731.1 2154.42  4738.8 2149.21
  4745.3 2147.57  4751.4 2143.55  4802.2 2131.29  4808.9 2126.34  4823.1 2124.63
  4829.8 2129.75  4837.3 2130.52  4844.0 2133.55  4922.0 2133.48  4943.6 2131.08
  4972.1 2120.85  4986.3 2121.05  4998.4 2117.48  4998.7 2116.98  5002.4 2117.48
  5014.8 2121.32  5042.3 2122.69  5078.4 2131.78  5113.6 2134.55  5127.8 2138.11
  5134.4 2142.72  5148.7 2146.66  5208.5 2149.85  5262.6 2150.09  5376.1 2161.41
#Mann=6,-1,0
  4705.5    0.16       0  4738.8    0.07       0  4751.4    0.16       0
  4998.4    0.07       0  5002.4    0.16       0  5208.5    0.07       0
Bank Sta=4998.4,5002.4
Exp/Cntr=0.3,0.1

Type RM Length L Ch R = 1,5908,83,83,83
BEGIN DESCRIPTION:
Elm 67 5908
END DESCRIPTION:
XS GIS Cut Line= 3
      1524316.96      6766131.13      1524546.16      6765997.44
      1524877.72      6765783.92
#Sta/Elev= 30
  4728.3 2157.47  4732.9 2156.83  4743.9 2154.07  4749.7 2149.50  4759.6 2147.39
  4765.4 2143.27  4781.1 2138.99  4802.6 2129.21  4818.3 2125.51  4830.2 2124.37
  4845.6 2131.31  4861.3 2129.06  4867.1 2131.70  4904.3 2132.10  4934.4 2129.56
  4957.3 2120.29  4963.1 2121.12  4988.1 2116.53  4988.3 2116.03  4992.1 2116.53
  5006.0 2116.78  5015.2 2120.61  5036.3 2121.42  5072.6 2131.81  5093.8 2132.83
  5099.7 2135.63  5165.7 2142.43  5281.3 2153.71  5296.5 2157.48  5388.0 2167.62
#Mann=5,-1,0
  4728.3    0.07       0  4732.9    0.16       0  4988.1    0.07       0
  4992.1    0.16       0  5165.7    0.07       0
Bank Sta=4988.1,4992.1
Exp/Cntr=0.3,0.1

Type RM Length L Ch R = 1,5825,74,74,74
BEGIN DESCRIPTION:
Elm 67 5824.75
END DESCRIPTION:
XS GIS Cut Line= 3
      1524318.73      6766179.73      1524560.05      6766075.56
      1524886.44      6765889.79
#Sta/Elev= 30
  4740.3 2171.92  4750.4 2169.52  4760.4 2166.49  4778.4 2156.60  4783.9 2155.24
  4790.7 2150.04  4807.4 2141.38  4854.4 2125.73  4883.4 2121.18  4930.4 2126.71
  4935.8 2124.06  4975.9 2121.11  5001.1 2115.60  5001.4 2115.10  5005.1 2115.60
  5033.1 2119.88  5070.5 2121.19  5092.2 2125.79  5108.0 2131.22  5172.9 2140.36
  5194.9 2141.43  5216.1 2144.47  5239.0 2144.46  5285.0 2148.77  5291.0 2151.57
  5312.7 2152.27  5342.5 2161.10  5371.8 2173.17  5375.5 2176.76  5378.7 2176.76
#Mann=5,-1,0
  4740.3    0.07       0  4750.4    0.16       0  5001.1    0.07       0
  5005.1    0.16       0  5194.9    0.07       0
Bank Sta=5001.1,5005.1
Exp/Cntr=0.3,0.1

Type RM Length L Ch R = 1,5751,119,119,119
BEGIN DESCRIPTION:
Elm 67 5750.53
END DESCRIPTION:
XS GIS Cut Line= 3
      1524323.96      6766195.35      1524599.98      6766136.32
      1524891.71      6766025.85
#Sta/Elev= 30
  4718.7 2170.53  4725.6 2169.95  4732.5 2168.99  4770.9 2151.45  4776.9 2147.09
  4791.3 2141.48  4852.7 2123.58  4870.7 2120.13  4903.8 2126.23  4914.1 2126.76
  4925.3 2130.22  4955.0 2123.39  4973.4 2115.90  4973.7 2115.40  4977.4 2115.90
  5017.0 2117.17  5049.1 2126.64  5182.3 2136.86  5206.1 2138.75  5220.2 2146.12
  5230.9 2146.20  5252.3 2155.50  5261.0 2161.42  5266.4 2161.93  5273.7 2167.70
  5284.3 2173.00  5291.2 2179.51  5296.5 2178.31  5305.7 2183.49  5312.9 2185.44
#Mann=5,-1,0
  4718.7    0.07       0  4725.6    0.16       0  4973.4    0.07       0
  4977.4    0.16       0  5182.3    0.07       0
Bank Sta=4973.4,4977.4
Exp/Cntr=0.3,0.1

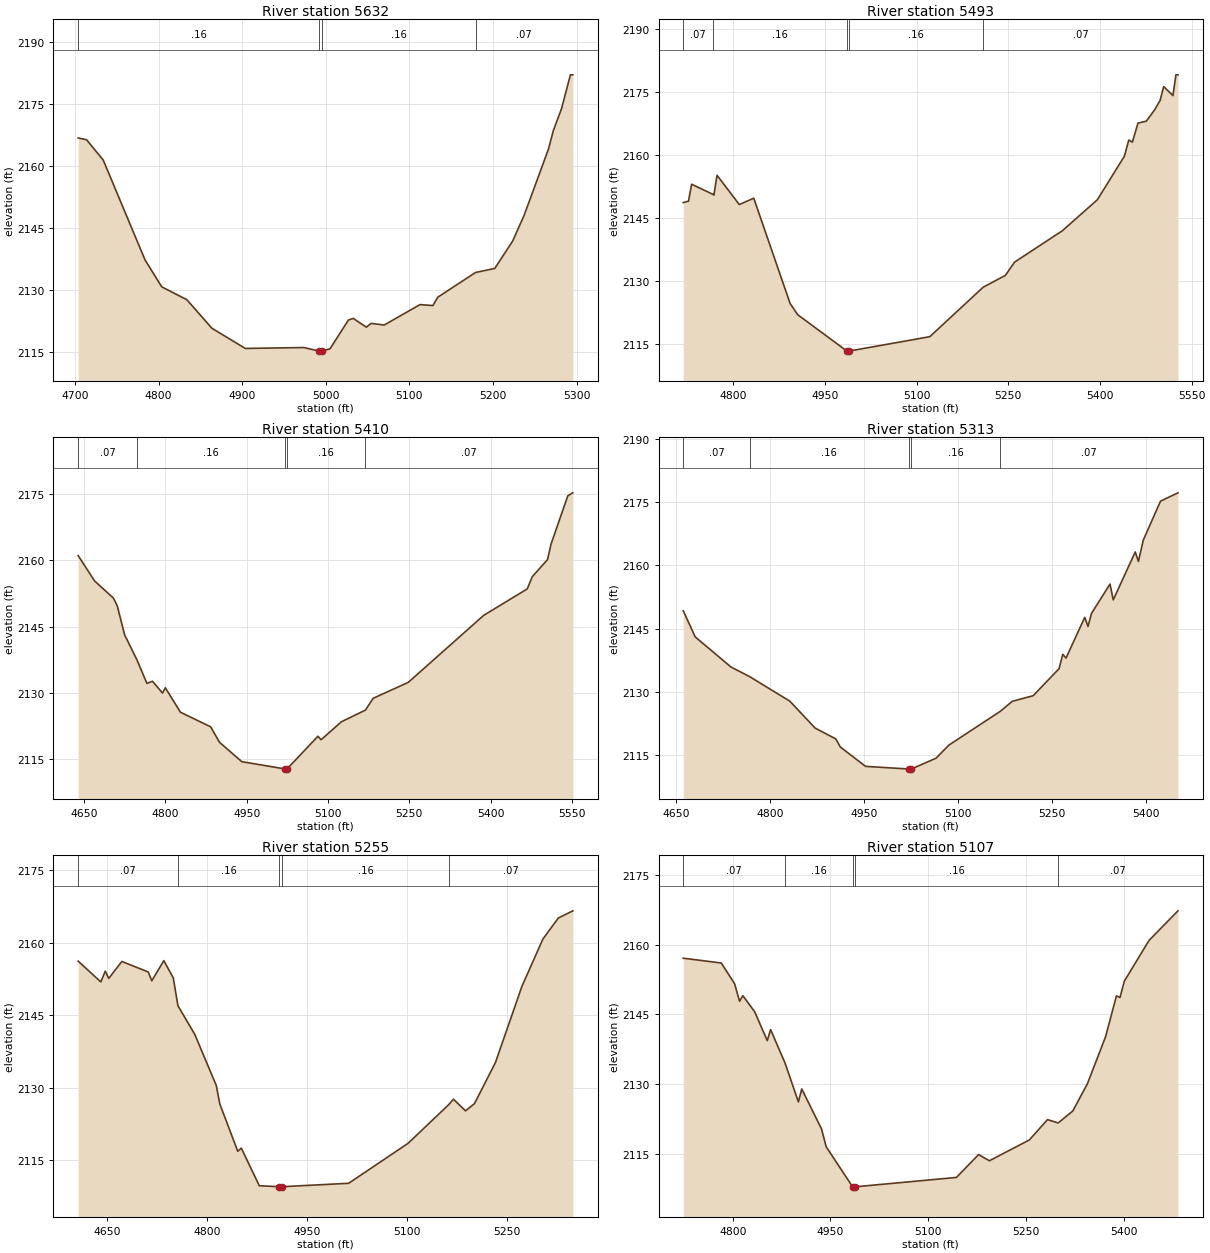
Type RM Length L Ch R = 1,5632,139,139,139
BEGIN DESCRIPTION:
Elm 67 5631.908
END DESCRIPTION:
XS GIS Cut Line= 3
      1524355.05      6766238.00      1524651.24      6766239.56
      1524905.02      6766087.99
#Sta/Elev= 30
  4703.8 2166.73  4713.8 2166.32  4733.8 2161.39  4783.8 2137.30  4803.8 2130.79
  4833.8 2127.69  4863.8 2120.80  4903.8 2115.92  4973.8 2116.14  4991.8 2115.29
  4992.0 2114.79  4995.8 2115.29  5005.1 2115.84  5027.1 2122.77  5032.9 2123.18
  5048.5 2121.06  5054.3 2121.97  5069.9 2121.57  5112.7 2126.50  5128.2 2126.28
  5134.1 2128.30  5179.2 2134.26  5202.2 2135.23  5223.6 2141.84  5237.3 2148.05
  5266.4 2164.01  5272.3 2168.54  5282.0 2173.75  5292.7 2181.97  5295.6 2181.97
#Mann=4,-1,0
  4703.8    0.16       0  4991.8    0.07       0  4995.8    0.16       0
  5179.2    0.07       0
Bank Sta=4991.8,4995.8
Exp/Cntr=0.3,0.1

Type RM Length L Ch R = 1,5493,83,83,83
BEGIN DESCRIPTION:
Elm 67 5492.84
END DESCRIPTION:
XS GIS Cut Line= 3
      1524382.97      6766445.35      1524659.01      6766377.64
      1525098.27      6766089.43
#Sta/Elev= 30
  4718.0 2148.71  4726.6 2149.05  4731.7 2153.07  4766.7 2150.66  4768.1 2150.49
  4773.3 2155.20  4809.7 2148.24  4833.4 2149.75  4892.9 2124.72  4905.4 2122.04
  4985.8 2113.42  4986.1 2112.92  4989.8 2113.42  5121.5 2116.83  5208.9 2128.60
  5245.1 2131.39  5260.2 2134.55  5338.6 2142.03  5395.8 2149.40  5440.0 2159.75
  5447.1 2163.57  5453.0 2163.07  5462.2 2167.60  5475.8 2168.07  5489.2 2170.71
  5498.3 2172.98  5504.3 2176.29  5519.4 2174.14  5524.3 2179.08  5527.6 2179.08
#Mann=5,-1,0
  4718.0    0.07       0  4766.7    0.16       0  4985.8    0.07       0
  4989.8    0.16       0  5208.9    0.07       0
Bank Sta=4985.8,4989.8
Exp/Cntr=0.3,0.1

Type RM Length L Ch R = 1,5410,97,97,97
BEGIN DESCRIPTION:
Elm 67 5410.42
END DESCRIPTION:
XS GIS Cut Line= 3
      1524351.74      6766530.41      1524702.41      6766445.35
      1525179.82      6766169.32
#Sta/Elev= 30
  4639.3 2161.07  4669.6 2155.33  4704.4 2151.44  4711.4 2149.71  4725.0 2143.14
  4747.5 2137.53  4766.1 2132.16  4776.4 2132.63  4794.9 2129.97  4800.1 2131.16
  4827.9 2125.63  4883.7 2122.32  4899.9 2118.84  4941.1 2114.44  5020.6 2112.80
  5020.9 2112.30  5024.6 2112.80  5081.5 2120.19  5087.3 2119.40  5124.6 2123.45
  5169.1 2126.11  5183.4 2128.78  5248.0 2132.37  5387.3 2147.55  5467.6 2153.53
  5476.7 2156.28  5504.9 2160.15  5511.4 2163.66  5542.3 2174.59  5551.6 2175.26
#Mann=5,-1,0
  4639.3    0.07       0  4747.5    0.16       0  5020.6    0.07       0
  5024.6    0.16       0  5169.1    0.07       0
Bank Sta=5020.6,5024.6
Exp/Cntr=0.3,0.1

Type RM Length L Ch R = 1,5313,58,58,58
BEGIN DESCRIPTION:
Elm 67 5313.32
END DESCRIPTION:
XS GIS Cut Line= 3
      1524376.06      6766582.50      1524714.56      6766540.84
      1525148.54      6766426.27
#Sta/Elev= 30
  4661.5 2149.20  4680.6 2143.02  4737.6 2135.90  4767.3 2133.63  4831.7 2127.80
  4872.0 2121.43  4905.1 2118.86  4912.3 2116.94  4952.6 2112.36  5021.7 2111.73
  5021.9 2111.23  5025.7 2111.73  5065.1 2114.29  5085.7 2117.40  5167.3 2125.35
  5187.0 2127.77  5220.2 2129.09  5261.6 2135.50  5267.5 2138.89  5272.7 2138.00
  5302.6 2147.65  5307.8 2145.49  5313.3 2148.57  5342.9 2155.53  5348.1 2151.79
  5383.2 2163.14  5388.3 2160.90  5396.0 2165.92  5423.5 2175.16  5451.4 2177.14
#Mann=5,-1,0
  4661.5    0.07       0  4767.3    0.16       0  5021.7    0.07       0
  5025.7    0.16       0  5167.3    0.07       0
Bank Sta=5021.7,5025.7
Exp/Cntr=0.3,0.1

Type RM Length L Ch R = 1,5255,148,148,148
BEGIN DESCRIPTION:
Elm 67 5255.34
END DESCRIPTION:
XS GIS Cut Line= 3
      1524372.57      6766705.76      1524754.49      6766584.24
      1525077.39      6766474.87
#Sta/Elev= 30
  4607.2 2156.18  4641.2 2151.88  4647.9 2154.11  4653.1 2152.61  4672.7 2156.11
  4712.3 2153.94  4717.6 2152.11  4735.7 2156.28  4749.8 2152.72  4756.8 2146.96
  4782.1 2141.01  4814.3 2130.45  4819.6 2126.63  4846.5 2116.83  4851.8 2117.49
  4878.8 2109.70  4909.0 2109.50  4909.2 2109.00  4913.0 2109.50  5012.8 2110.21
  5101.8 2118.47  5162.7 2126.47  5169.9 2127.61  5188.0 2125.20  5201.4 2126.69
  5232.8 2135.18  5272.5 2150.95  5304.1 2160.77  5327.1 2165.10  5348.9 2166.59
#Mann=5,-1,0
  4607.2    0.07       0  4756.8    0.16       0  4909.0    0.07       0
  4913.0    0.16       0  5162.7    0.07       0
Bank Sta=4909,4913
Exp/Cntr=0.3,0.1

Type RM Length L Ch R = 1,5107,77,77,77
BEGIN DESCRIPTION:
Elm 67 5106.72
END DESCRIPTION:
XS GIS Cut Line= 3
      1524388.15      6766763.07      1524657.27      6766700.56
      1525088.42      6766482.39
#Sta/Elev= 30
  4724.0 2157.09  4782.4 2156.06  4802.9 2151.58  4810.4 2147.82  4815.5 2149.02
  4833.7 2145.55  4853.0 2139.34  4858.1 2141.71  4880.2 2134.55  4900.8 2126.15
  4905.9 2128.94  4936.4 2120.29  4943.4 2116.50  4984.0 2107.87  4984.3 2107.37
  4988.0 2107.87  5143.4 2109.89  5177.4 2114.81  5194.0 2113.48  5255.3 2117.95
  5283.2 2122.33  5299.6 2121.62  5322.1 2124.20  5344.4 2130.03  5372.3 2140.14
  5389.0 2148.96  5394.6 2148.65  5401.2 2152.15  5439.1 2160.92  5483.5 2167.29
#Mann=5,-1,0
  4724.0    0.07       0  4880.2    0.16       0  4984.0    0.07       0
  4988.0    0.16       0  5299.6    0.07       0
Bank Sta=4984,4988
Exp/Cntr=0.3,0.1

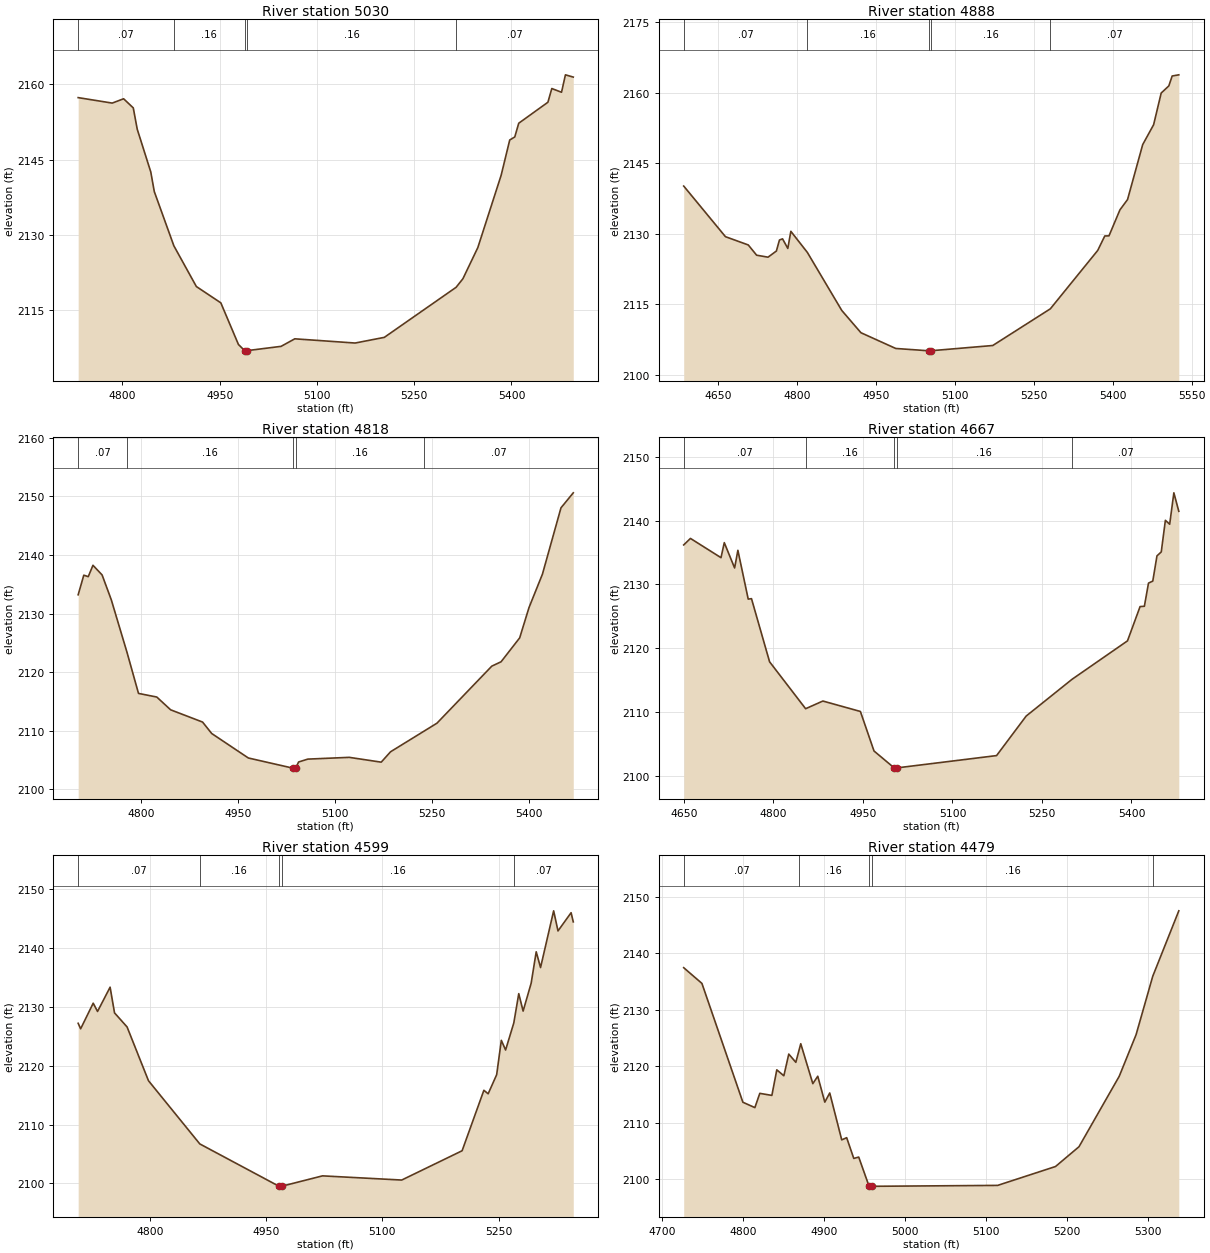
Type RM Length L Ch R = 1,5030,142,142,142
BEGIN DESCRIPTION:
Elm 67 5029.56
END DESCRIPTION:
XS GIS Cut Line= 3
      1524428.09      6766848.14      1524688.52      6766766.53
      1525096.52      6766493.95
#Sta/Elev= 30
  4731.7 2157.35  4784.2 2156.26  4801.8 2157.12  4816.7 2155.30  4822.8 2151.06
  4843.7 2142.54  4849.1 2138.64  4879.3 2127.83  4914.0 2119.72  4951.7 2116.48
  4978.9 2108.18  4988.5 2106.96  4988.7 2106.46  4992.5 2106.96  5044.7 2107.81
  5065.8 2109.31  5158.9 2108.47  5203.9 2109.60  5314.6 2119.57  5325.1 2121.28
  5348.1 2127.48  5384.1 2141.90  5397.3 2148.91  5405.1 2149.52  5411.2 2152.25
  5456.2 2156.43  5462.2 2159.16  5477.2 2158.42  5483.2 2161.89  5495.3 2161.44
#Mann=5,-1,0
  4731.7    0.07       0  4879.3    0.16       0  4988.5    0.07       0
  4992.5    0.16       0  5314.6    0.07       0
Bank Sta=4988.5,4992.5
Exp/Cntr=0.3,0.1

Type RM Length L Ch R = 1,4888,70,70,70
BEGIN DESCRIPTION:
Elm 67 4888.05
END DESCRIPTION:
XS GIS Cut Line= 3
      1524421.12      6767072.11      1524785.74      6766867.23
      1525195.84      6766541.92
#Sta/Elev= 30
  4583.9 2140.14  4663.3 2129.37  4706.7 2127.61  4722.6 2125.43  4744.3 2125.01
  4760.2 2126.32  4766.0 2128.66  4771.9 2128.91  4781.9 2126.87  4787.7 2130.51
  4819.1 2126.02  4884.6 2113.67  4921.0 2108.94  4987.2 2105.59  5049.5 2105.10
  5049.8 2104.60  5053.5 2105.10  5171.7 2106.22  5281.2 2114.02  5371.4 2126.45
  5384.8 2129.52  5392.8 2129.55  5413.6 2135.07  5428.1 2137.27  5456.9 2148.95
  5477.7 2153.19  5492.1 2159.93  5506.6 2161.44  5513.0 2163.55  5525.6 2163.80
#Mann=5,-1,0
  4583.9    0.07       0  4819.1    0.16       0  5049.5    0.07       0
  5053.5    0.16       0  5281.2    0.07       0
Bank Sta=5049.5,5053.5
Exp/Cntr=0.3,0.1

Type RM Length L Ch R = 1,4818,151,151,151
BEGIN DESCRIPTION:
Elm 67 4817.59
END DESCRIPTION:
XS GIS Cut Line= 3
      1524617.33      6767122.45      1524836.09      6766915.84
      1525196.82      6766622.74
#Sta/Elev= 30
  4702.6 2133.22  4711.3 2136.56  4718.2 2136.31  4725.5 2138.25  4739.6 2136.60
  4753.8 2132.37  4778.2 2123.37  4795.9 2116.39  4824.2 2115.77  4845.6 2113.59
  4895.0 2111.50  4909.1 2109.55  4965.8 2105.37  5035.0 2103.63  5035.3 2103.13
  5039.0 2103.63  5043.5 2104.69  5057.8 2105.18  5121.8 2105.48  5171.3 2104.66
  5185.7 2106.43  5237.2 2109.93  5257.5 2111.31  5342.3 2121.04  5356.7 2121.79
  5385.4 2125.86  5399.8 2131.02  5420.6 2136.73  5449.3 2148.05  5468.3 2150.61
#Mann=5,-1,0
  4702.6    0.07       0  4778.2    0.16       0  5035.0    0.07       0
  5039.0    0.16       0  5237.2    0.07       0
Bank Sta=5035,5039
Exp/Cntr=0.3,0.1

Type RM Length L Ch R = 1,4667,68,68,68
BEGIN DESCRIPTION:
Elm 67 4667.27
END DESCRIPTION:
XS GIS Cut Line= 3
      1524594.73      6767190.16      1524909.01      6767042.57
      1525254.49      6766705.77
#Sta/Elev= 30
  4649.6 2136.18  4660.9 2137.20  4712.1 2134.19  4717.6 2136.54  4734.9 2132.58
  4740.4 2135.34  4757.7 2127.71  4763.2 2127.78  4793.5 2117.91  4853.9 2110.57
  4882.8 2111.77  4945.7 2110.14  4968.5 2103.96  5002.4 2101.31  5002.6 2100.81
  5006.4 2101.31  5173.9 2103.24  5223.5 2109.42  5300.4 2115.17  5393.3 2121.18
  5414.4 2126.54  5421.6 2126.59  5428.5 2130.21  5435.7 2130.53  5442.7 2134.47
  5449.9 2135.09  5456.8 2140.03  5464.0 2139.42  5471.0 2144.33  5479.3 2141.44
#Mann=5,-1,0
  4649.6    0.07       0  4853.9    0.16       0  5002.4    0.07       0
  5006.4    0.16       0  5300.4    0.07       0
Bank Sta=5002.4,5006.4
Exp/Cntr=0.3,0.1

Type RM Length L Ch R = 1,4599,120,120,120
BEGIN DESCRIPTION:
Elm 67 4598.68
END DESCRIPTION:
XS GIS Cut Line= 3
      1524695.45      6767233.55      1524952.41      6767094.66
      1525263.80      6766942.42
#Sta/Elev= 30
  4707.6 2127.17  4710.8 2126.24  4727.0 2130.58  4732.6 2129.18  4748.8 2133.30
  4754.5 2128.94  4770.7 2126.55  4798.3 2117.43  4864.5 2106.71  4966.5 2099.54
  4966.8 2099.04  4970.5 2099.54  5022.8 2101.29  5125.0 2100.58  5202.9 2105.55
  5231.0 2115.81  5236.5 2115.21  5247.5 2118.46  5253.5 2124.28  5259.0 2122.64
  5269.6 2127.24  5276.0 2132.20  5281.6 2129.24  5292.0 2133.98  5298.5 2139.30
  5304.1 2136.63  5321.0 2146.25  5326.6 2142.84  5343.5 2145.93  5346.3 2144.38
#Mann=5,-1,0
  4707.6    0.07       0  4864.5    0.16       0  4966.5    0.07       0
  4970.5    0.16       0  5269.6    0.07       0
Bank Sta=4966.5,4970.5
Exp/Cntr=0.3,0.1

Type RM Length L Ch R = 1,4479,129,129,129
BEGIN DESCRIPTION:
Elm 67 4478.77
END DESCRIPTION:
XS GIS Cut Line= 3
      1524750.98      6767365.52      1524969.77      6767212.71
      1525241.14      6767000.11
#Sta/Elev= 30
  4726.3 2137.43  4748.8 2134.65  4799.4 2113.63  4814.2 2112.68  4820.3 2115.20
  4835.2 2114.84  4841.3 2119.36  4850.0 2118.31  4856.1 2122.15  4864.8 2120.69
  4868.7 2122.79  4870.9 2123.98  4885.8 2116.92  4891.9 2118.23  4900.6 2113.65
  4906.7 2115.27  4921.5 2106.97  4927.6 2107.36  4936.4 2103.69  4942.5 2103.93
  4955.3 2098.76  4955.5 2098.26  4959.3 2098.76  5114.1 2098.92  5185.6 2102.26
  5214.6 2105.76  5264.3 2118.22  5285.1 2125.57  5305.7 2135.91  5337.9 2147.49
#Mann=5,-1,0
  4726.3    0.07       0  4868.7    0.16       0  4955.3    0.07       0
  4959.3    0.16       0  5305.7    0.07       0
Bank Sta=4955.3,4959.3
Exp/Cntr=0.3,0.1

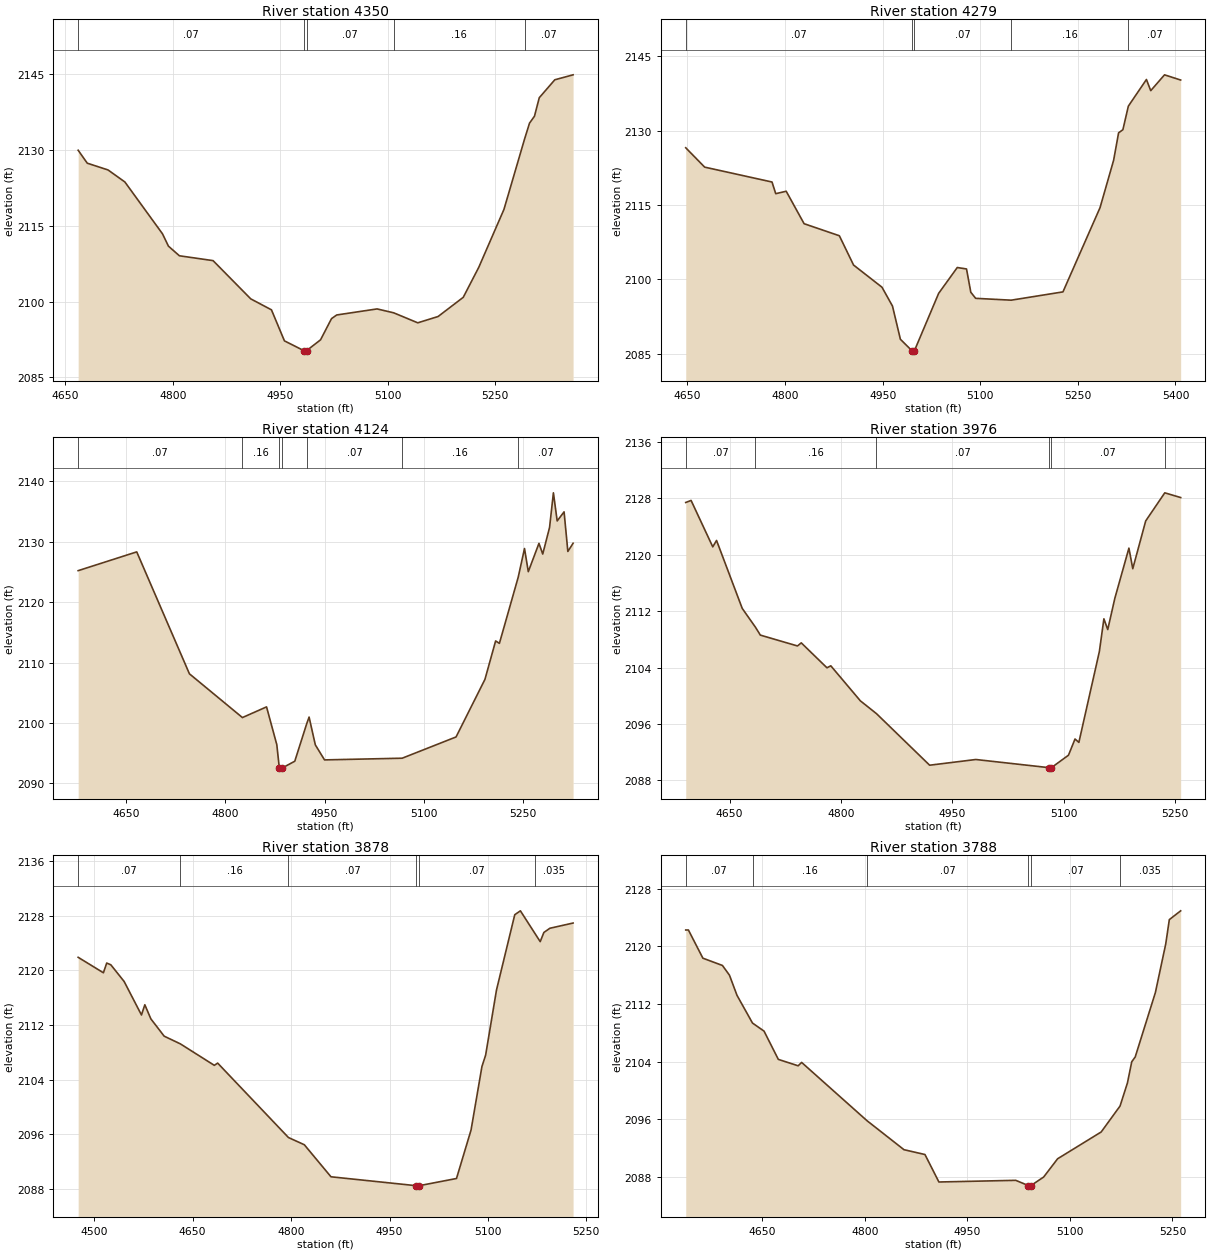
Type RM Length L Ch R = 1,4350,71,71,71
BEGIN DESCRIPTION:
Elm 67 4349.57
END DESCRIPTION:
XS GIS Cut Line= 3
      1524749.28      6767438.41      1525060.05      6767304.73
      1525295.95      6767042.81
#Sta/Elev= 30
  4667.8 2129.95  4680.5 2127.39  4709.5 2126.05  4733.0 2123.67  4785.5 2113.41
  4793.8 2110.97  4809.1 2109.06  4856.1 2108.10  4908.7 2100.53  4937.6 2098.36
  4955.7 2092.22  4982.7 2090.29  4983.0 2089.79  4986.7 2090.29  5006.1 2092.42
  5021.4 2096.61  5028.6 2097.34  5085.0 2098.54  5108.2 2097.77  5141.8 2095.79
  5170.2 2097.04  5205.3 2100.84  5227.0 2106.79  5262.1 2118.24  5290.9 2132.18
  5297.8 2135.32  5304.7 2136.69  5311.4 2140.35  5333.1 2143.90  5358.6 2144.88
#Mann=5,-1,0
  4667.8    0.07       0  4982.7    0.07       0  4986.7    0.07       0
  5108.2    0.16       0  5290.9    0.07       0
Bank Sta=4982.7,4986.7
Exp/Cntr=0.3,0.1

Type RM Length L Ch R = 1,4279,155,155,155
BEGIN DESCRIPTION:
Elm 67 4278.53
END DESCRIPTION:
XS GIS Cut Line= 3
      1524775.31      6767537.37      1525084.35      6767368.96
      1525350.87      6767059.18
#Sta/Elev= 30
  4647.4 2126.52  4676.5 2122.62  4780.0 2119.62  4785.7 2117.27  4801.8 2117.76
  4829.3 2111.22  4883.5 2108.79  4905.3 2102.89  4949.0 2098.42  4965.1 2094.63
  4977.3 2087.93  4994.9 2085.64  4995.1 2085.14  4998.9 2085.64  5036.1 2097.19
  5064.7 2102.39  5078.9 2102.10  5085.5 2097.40  5093.0 2096.18  5147.6 2095.81
  5227.1 2097.48  5284.1 2114.46  5305.0 2124.02  5312.6 2129.53  5319.2 2130.16
  5327.6 2134.91  5355.4 2140.28  5362.0 2138.03  5383.2 2141.22  5408.0 2140.17
#Mann=5,-1,0
  4647.4    0.07       0  4994.9    0.07       0  4998.9    0.07       0
  5147.6    0.16       0  5327.6    0.07       0
Bank Sta=4994.9,4998.9
Exp/Cntr=0.3,0.1

Type RM Length L Ch R = 1,4124,148,148,148
BEGIN DESCRIPTION:
Elm 67 4124.22
END DESCRIPTION:
XS GIS Cut Line= 3
      1524856.96      6767570.33      1525218.03      6767351.60
      1525374.26      6767066.91
#Sta/Elev= 30
  4578.2 2125.21  4666.6 2128.32  4746.1 2108.13  4826.1 2100.88  4862.5 2102.65
  4878.0 2096.38  4881.8 2092.51  4882.1 2092.01  4885.8 2092.51  4905.1 2093.65
  4923.1 2099.86  4926.7 2100.96  4936.1 2096.36  4950.0 2093.87  5067.2 2094.15
  5148.5 2097.67  5192.1 2107.21  5208.2 2113.57  5213.9 2113.17  5242.3 2124.13
  5251.8 2128.88  5257.5 2125.04  5273.6 2129.73  5279.3 2127.96  5289.6 2132.37
  5295.4 2138.10  5301.1 2133.44  5311.5 2134.95  5317.2 2128.39  5325.1 2129.75
#Mann=7,-1,0
  4578.2    0.07       0  4826.1    0.16       0  4881.8    0.07       0
  4885.8    0.16       0  4923.1    0.07       0  5067.2    0.16       0
  5242.3    0.07       0
Bank Sta=4881.8,4885.8
Exp/Cntr=0.3,0.1

Type RM Length L Ch R = 1,3976,98,98,98
BEGIN DESCRIPTION:
Elm 67 3976.3
END DESCRIPTION:
XS GIS Cut Line= 3
      1524928.08      6767563.41      1525316.99      6767457.50
      1525570.24      6767384.65
#Sta/Elev= 30
  4590.9 2127.43  4598.1 2127.72  4627.3 2121.13  4632.4 2122.04  4667.0 2112.39
  4684.8 2109.72  4691.4 2108.60  4741.4 2107.06  4746.5 2107.50  4781.1 2103.96
  4786.3 2104.24  4826.1 2099.27  4847.8 2097.45  4919.4 2090.13  4981.6 2090.94
  5079.5 2089.79  5079.7 2089.29  5083.5 2089.79  5106.4 2091.55  5115.2 2093.85
  5120.4 2093.37  5148.0 2106.27  5154.1 2110.91  5159.3 2109.39  5168.8 2113.81
  5187.8 2120.95  5193.0 2118.03  5210.4 2124.81  5236.1 2128.80  5257.5 2128.13
#Mann=6,-1,0
  4590.9    0.07       0  4684.8    0.16       0  4847.8    0.07       0
  5079.5    0.07       0  5083.5    0.07       0  5236.1   0.035       0
Bank Sta=5079.5,5083.5
Exp/Cntr=0.3,0.1

Type RM Length L Ch R = 1,3878,90,90,90
BEGIN DESCRIPTION:
Elm 67 3878.21
END DESCRIPTION:
XS GIS Cut Line= 3
      1524876.05      6767620.69      1525393.38      6767525.21
      1525596.47      6767421.07
#Sta/Elev= 30
  4475.5 2121.93  4514.0 2119.66  4519.0 2121.09  4525.3 2120.83  4545.6 2118.38
  4572.0 2113.47  4577.1 2114.97  4586.3 2112.90  4606.6 2110.36  4631.3 2109.23
  4683.0 2106.08  4688.1 2106.41  4796.0 2095.49  4820.2 2094.43  4860.8 2089.73
  4991.0 2088.42  4991.3 2087.92  4995.0 2088.42  5052.1 2089.48  5074.3 2096.60
  5090.9 2105.92  5096.5 2107.57  5113.1 2117.15  5140.9 2128.18  5149.5 2128.75
  5171.0 2125.53  5179.7 2124.23  5185.3 2125.58  5194.4 2126.19  5229.8 2126.96
#Mann=6,-1,0
  4475.5    0.07       0  4631.3    0.16       0  4796.0    0.07       0
  4991.0    0.07       0  4995.0    0.07       0  5171.0   0.035       0
Bank Sta=4991,4995
Exp/Cntr=0.3,0.1

Type RM Length L Ch R = 1,3788,65,65,65
BEGIN DESCRIPTION:
Elm 67 3787.77
END DESCRIPTION:
XS GIS Cut Line= 3
      1524952.40      6767707.51      1525407.27      6767612.02
      1525661.20      6767558.47
#Sta/Elev= 30
  4537.7 2122.25  4541.6 2122.25  4562.8 2118.34  4591.4 2117.33  4601.7 2115.98
  4612.7 2113.19  4635.4 2109.34  4652.3 2108.22  4673.2 2104.30  4702.2 2103.41
  4707.3 2103.88  4802.9 2095.80  4857.1 2091.77  4887.8 2091.10  4908.2 2087.29
  5020.6 2087.52  5039.0 2086.80  5039.3 2086.30  5043.0 2086.80  5061.5 2087.98
  5081.9 2090.51  5145.7 2094.23  5173.3 2097.83  5184.1 2101.03  5190.4 2103.97
  5195.5 2104.64  5225.0 2113.57  5240.2 2120.34  5245.4 2123.69  5262.0 2124.91
#Mann=6,-1,0
  4537.7    0.07       0  4635.4    0.16       0  4802.9    0.07       0
  5039.0    0.07       0  5043.0    0.07       0  5173.3   0.035       0
Bank Sta=5039,5043
Exp/Cntr=0.3,0.1

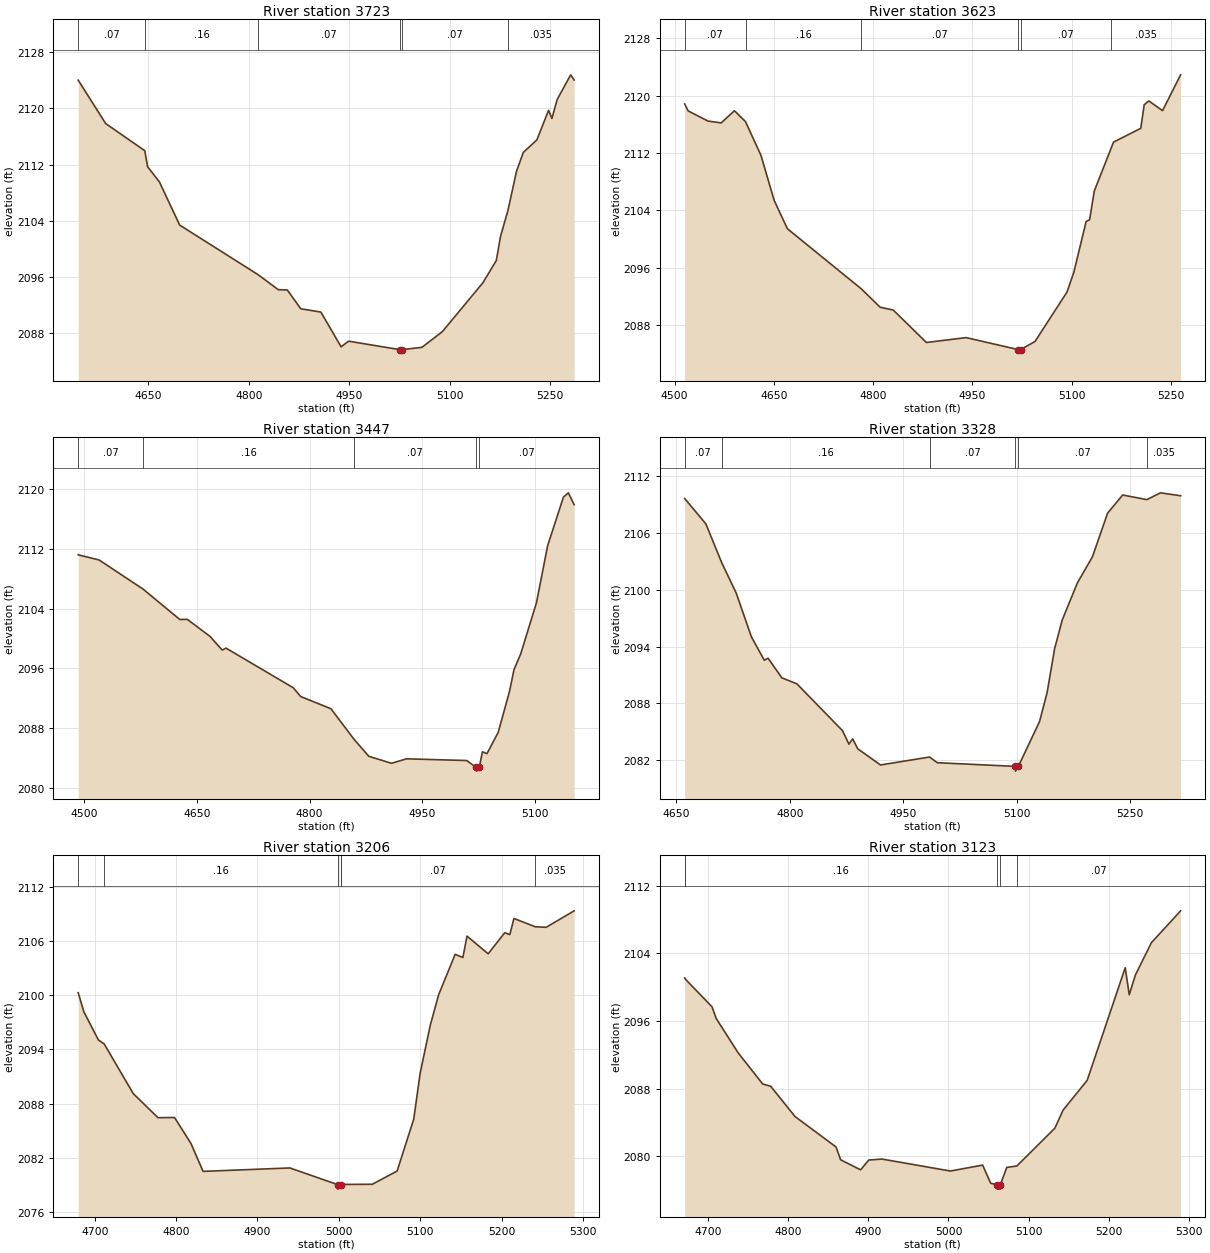
Type RM Length L Ch R = 1,3723,100,100,100
BEGIN DESCRIPTION:
Elm 67 3722.85
END DESCRIPTION:
XS GIS Cut Line= 3
      1524954.19      6767723.12      1525402.06      6767677.99
      1525690.17      6767638.07
#Sta/Elev= 30
  4545.1 2124.02  4586.1 2117.85  4644.5 2113.99  4648.8 2111.70  4666.5 2109.53
  4696.7 2103.40  4814.1 2096.33  4844.0 2094.21  4857.5 2094.17  4877.6 2091.49
  4907.7 2091.02  4937.9 2086.08  4949.1 2086.88  5025.5 2085.68  5025.8 2085.18
  5029.5 2085.68  5058.8 2086.01  5089.1 2088.23  5149.6 2095.17  5169.8 2098.36
  5176.1 2101.78  5187.0 2105.42  5200.1 2111.09  5210.2 2113.75  5230.4 2115.52
  5247.9 2119.73  5252.9 2118.58  5260.7 2121.26  5280.9 2124.78  5286.1 2124.04
#Mann=6,-1,0
  4545.1    0.07       0  4644.5    0.16       0  4814.1    0.07       0
  5025.5    0.07       0  5029.5    0.07       0  5187.0   0.035       0
Bank Sta=5025.5,5029.5
Exp/Cntr=0.3,0.1

Type RM Length L Ch R = 1,3623,176,176,176
BEGIN DESCRIPTION:
Elm 67 3623.08
END DESCRIPTION:
XS GIS Cut Line= 3
      1524969.81      6767761.32      1525462.82      6767761.32
      1525711.46      6767699.17
#Sta/Elev= 30
  4515.2 2118.84  4520.4 2117.87  4550.4 2116.45  4570.4 2116.20  4590.4 2117.89
  4607.1 2116.37  4630.4 2111.69  4650.4 2105.41  4670.4 2101.46  4782.2 2093.08
  4810.4 2090.54  4830.4 2090.13  4880.4 2085.62  4940.4 2086.30  5018.8 2084.64
  5019.0 2084.14  5022.8 2084.64  5044.5 2085.76  5092.9 2092.65  5103.2 2095.41
  5121.8 2102.48  5127.0 2102.71  5134.1 2106.72  5159.1 2112.57  5163.1 2113.52
  5204.3 2115.44  5209.5 2118.73  5216.6 2119.25  5237.2 2117.90  5264.5 2122.89
#Mann=6,-1,0
  4515.2    0.07       0  4607.1    0.16       0  4782.2    0.07       0
  5018.8    0.07       0  5022.8    0.07       0  5159.1   0.035       0
Bank Sta=5018.8,5022.8
Exp/Cntr=0.3,0.1

Type RM Length L Ch R = 1,3447,119,119,119
BEGIN DESCRIPTION:
Elm 67 3446.83
END DESCRIPTION:
XS GIS Cut Line= 3
      1524950.71      6767849.87      1525454.14      6767910.63
      1525581.34      6767824.68
#Sta/Elev= 30
  4491.8 2111.22  4519.6 2110.53  4578.1 2106.63  4627.1 2102.55  4637.1 2102.57
  4667.4 2100.28  4683.6 2098.45  4688.7 2098.71  4778.2 2093.40  4788.2 2092.22
  4828.5 2090.58  4859.0 2086.51  4878.9 2084.21  4909.1 2083.27  4929.2 2083.87
  5009.2 2083.64  5022.1 2082.72  5022.3 2082.22  5026.1 2082.72  5030.2 2084.81
  5036.3 2084.57  5051.2 2087.40  5066.2 2092.86  5072.3 2095.83  5081.2 2097.93
  5102.2 2104.79  5117.1 2112.44  5138.1 2118.95  5144.7 2119.53  5152.4 2117.94
#Mann=5,-1,0
  4491.8    0.07       0  4578.1    0.16       0  4859.0    0.07       0
  5022.1    0.07       0  5026.1    0.07       0
Bank Sta=5022.1,5026.1
Exp/Cntr=0.3,0.1

Type RM Length L Ch R = 1,3328,122,122,122
BEGIN DESCRIPTION:
Elm 67 3327.9
END DESCRIPTION:
XS GIS Cut Line= 3
      1525067.03      6767983.55      1525400.32      6768013.06
      1525721.63      6768013.06
#Sta/Elev= 30
  4661.1 2109.65  4689.2 2106.96  4710.0 2102.88  4729.3 2099.65  4749.4 2095.02
  4766.4 2092.56  4771.4 2092.77  4789.6 2090.70  4809.6 2090.06  4869.9 2085.11
  4878.3 2083.69  4883.3 2084.25  4890.0 2083.20  4920.1 2081.49  4984.9 2082.33
  4995.2 2081.73  5098.4 2081.34  5098.6 2080.84  5102.4 2081.34  5130.4 2086.07
  5140.4 2089.12  5150.4 2093.79  5160.4 2096.80  5180.4 2100.72  5200.4 2103.49
  5220.4 2108.10  5240.4 2110.02  5272.3 2109.53  5290.4 2110.25  5317.0 2109.94
#Mann=6,-1,0
  4661.1    0.07       0  4710.0    0.16       0  4984.9    0.07       0
  5098.4    0.07       0  5102.4    0.07       0  5272.3   0.035       0
Bank Sta=5098.4,5102.4
Exp/Cntr=0.3,0.1

Type RM Length L Ch R = 1,3206,83,83,83
BEGIN DESCRIPTION:
Elm 67 3205.72
END DESCRIPTION:
XS GIS Cut Line= 3
      1525138.15      6768068.61      1525461.09      6768120.70
      1525738.84      6768068.62
#Sta/Elev= 30
  4679.6 2100.30  4686.5 2098.19  4704.4 2095.06  4711.5 2094.62  4747.3 2089.10
  4777.7 2086.43  4798.0 2086.45  4818.2 2083.57  4833.1 2080.47  4939.8 2080.85
  4998.5 2079.00  4998.8 2078.50  5002.5 2079.00  5002.9 2079.02  5041.2 2079.04
  5071.7 2080.51  5092.1 2086.27  5100.0 2091.37  5112.4 2096.68  5122.6 2100.05
  5143.0 2104.56  5152.5 2104.21  5157.6 2106.58  5183.6 2104.62  5204.0 2106.96
  5210.2 2106.75  5215.3 2108.54  5241.6 2107.62  5254.9 2107.56  5289.3 2109.39
#Mann=6,-1,0
  4679.6    0.07       0  4711.5    0.16       0  4998.5    0.07       0
  5002.5    0.16       0  5002.9    0.07       0  5241.6   0.035       0
Bank Sta=4998.5,5002.5
Exp/Cntr=0.3,0.1

Type RM Length L Ch R = 1,3123,154,154,154
BEGIN DESCRIPTION:
Elm 67 3122.95
END DESCRIPTION:
XS GIS Cut Line= 3
      1525089.52      6768125.90      1525421.16      6768190.14
      1525701.25      6768167.67
#Sta/Elev= 30
  4670.9 2101.10  4671.6 2100.97  4705.1 2097.68  4710.2 2096.31  4737.6 2092.25
  4768.2 2088.57  4778.3 2088.29  4808.6 2084.72  4859.8 2081.12  4865.5 2079.61
  4890.4 2078.42  4900.6 2079.58  4917.2 2079.69  5002.4 2078.28  5042.7 2078.98
  5052.7 2076.84  5060.7 2076.64  5061.0 2076.14  5064.5 2076.14  5064.7 2076.64
  5072.8 2078.71  5085.3 2078.87  5132.9 2083.35  5143.0 2085.47  5173.1 2088.99
  5220.6 2102.31  5225.6 2099.11  5233.3 2101.45  5253.3 2105.27  5289.7 2109.03
#Mann=5,-1,0
  4670.9    0.07       0  4671.6    0.16       0  5060.7    0.07       0
  5064.7    0.16       0  5085.3    0.07       0
Bank Sta=5060.7,5064.7
Exp/Cntr=0.3,0.1