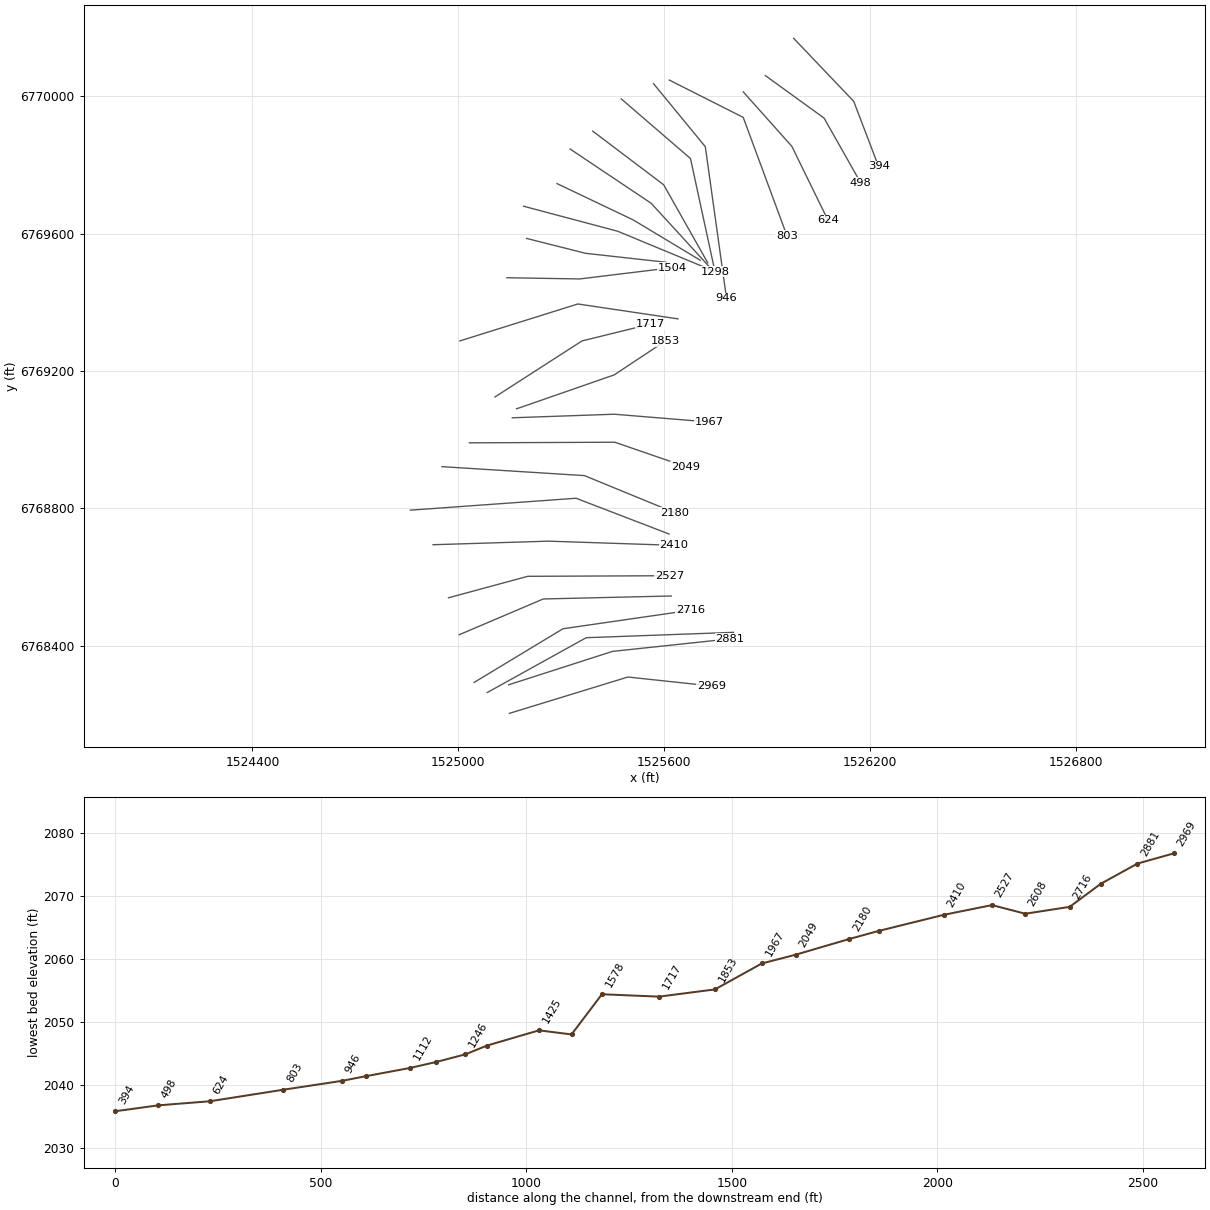
HEC-RAS study Elm 67.prj: Elm 67 Base Level Engineering

--- Elm 67.g01 (geometry) --- (continued)

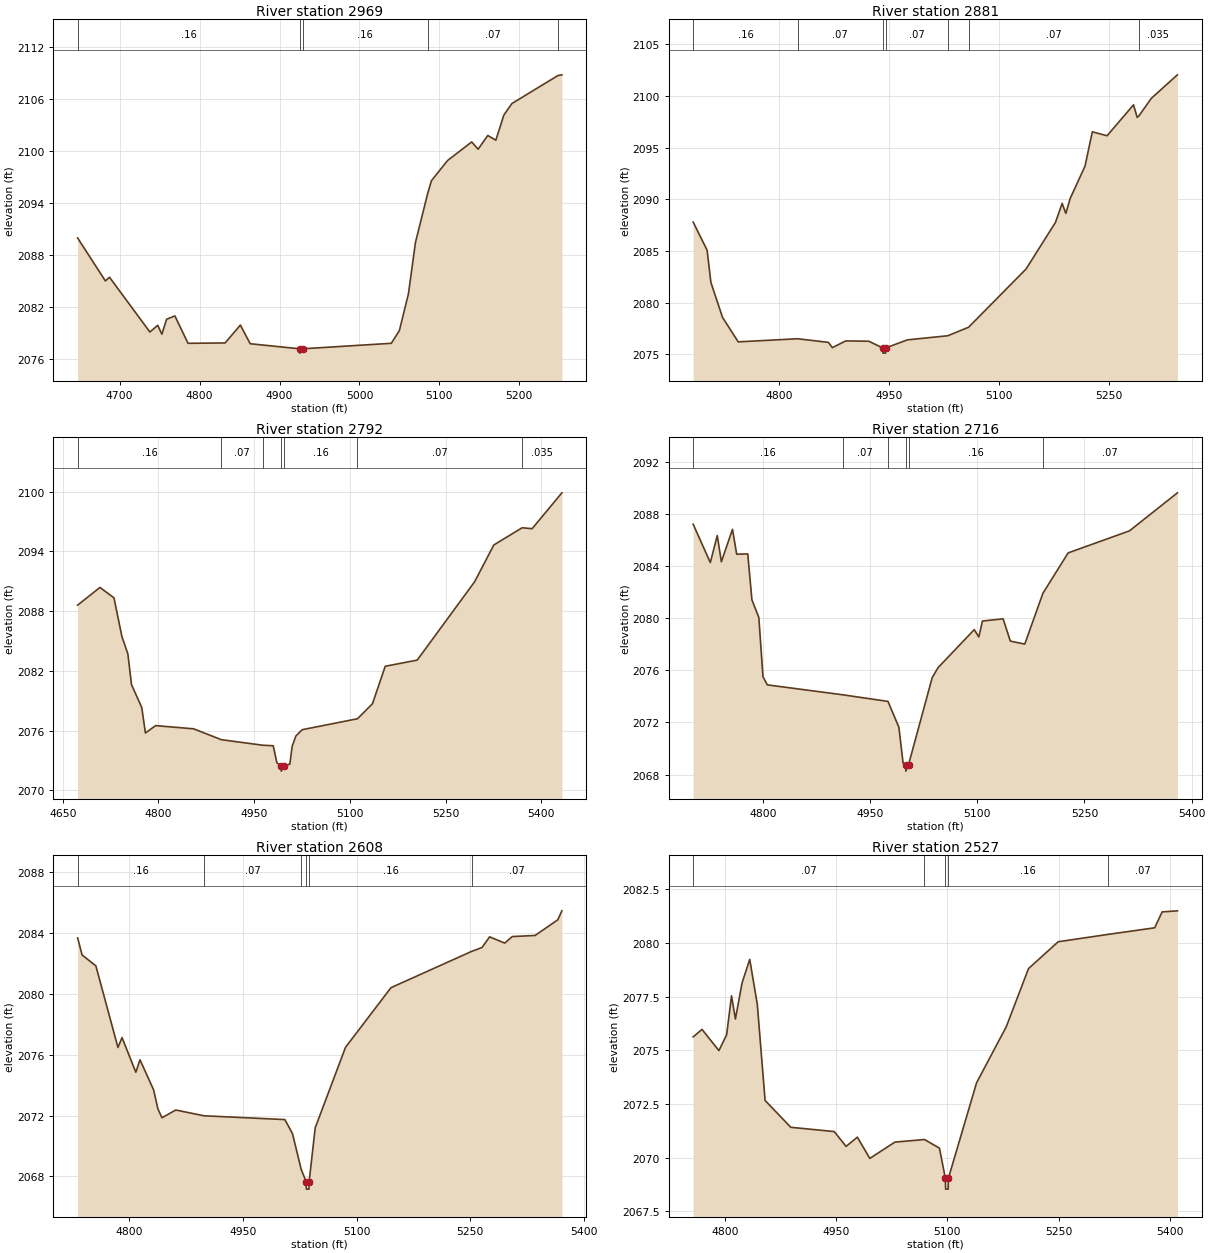
Type RM Length L Ch R = 1,2969,88,88,88
BEGIN DESCRIPTION:
Elm 67 2969.08
END DESCRIPTION:
XS GIS Cut Line= 3
      1525148.62      6768202.31      1525494.07      6768308.20
      1525737.16      6768282.15
#Sta/Elev= 30
  4647.4 2089.98  4682.1 2085.04  4687.3 2085.46  4737.8 2079.16  4747.6 2079.93
  4752.8 2078.91  4758.7 2080.63  4769.1 2081.01  4785.5 2077.86  4831.9 2077.90
  4851.0 2079.96  4863.3 2077.81  4925.0 2077.23  4925.2 2076.73  4929.0 2077.23
  5039.8 2077.86  5049.9 2079.32  5061.2 2083.54  5070.0 2089.45  5085.4 2095.13
  5090.1 2096.58  5110.2 2098.89  5140.4 2101.03  5148.4 2100.19  5160.5 2101.77
  5170.6 2101.23  5180.6 2104.12  5190.7 2105.45  5248.3 2108.67  5253.2 2108.75
#Mann=5,-1,0
  4647.4    0.16       0  4925.0    0.07       0  4929.0    0.16       0
  5085.4    0.07       0  5248.3   0.035       0
Bank Sta=4925,4929
Exp/Cntr=0.3,0.1

Type RM Length L Ch R = 1,2881,89,89,89
BEGIN DESCRIPTION:
Elm 67 2881.23
END DESCRIPTION:
XS GIS Cut Line= 3
      1525146.83      6768285.62      1525448.94      6768382.85
      1525790.43      6768419.26
#Sta/Elev= 30
  4683.2 2087.79  4702.2 2085.08  4707.4 2081.96  4723.3 2078.57  4744.7 2076.21
  4825.7 2076.51  4867.8 2076.16  4873.1 2075.65  4891.4 2076.30  4922.9 2076.27
  4941.9 2075.62  4942.2 2075.12  4945.7 2075.12  4945.9 2075.62  4975.4 2076.40
  5030.6 2076.80  5059.0 2077.62  5137.4 2083.25  5177.6 2087.76  5186.7 2089.60
  5191.7 2088.63  5197.7 2090.08  5217.9 2093.20  5227.9 2096.52  5248.0 2096.14
  5284.1 2099.13  5289.1 2097.91  5291.6 2098.07  5308.4 2099.76  5344.0 2102.03
#Mann=7,-1,0
  4683.2    0.16       0  4825.7    0.07       0  4941.9    0.07       0
  4945.9    0.07       0  5030.6    0.16       0  5059.0    0.07       0
  5291.6   0.035       0
Bank Sta=4941.9,4945.9
Exp/Cntr=0.3,0.1

Type RM Length L Ch R = 1,2792,76,76,76
BEGIN DESCRIPTION:
Elm 67 2791.71
END DESCRIPTION:
XS GIS Cut Line= 3
      1525084.37      6768263.07      1525372.55      6768422.78
      1525801.58      6768438.35
#Sta/Elev= 30
  4673.4 2088.60  4708.4 2090.38  4730.4 2089.33  4742.7 2085.47  4752.1 2083.71
  4757.8 2080.62  4773.9 2078.32  4779.6 2075.76  4795.6 2076.50  4855.1 2076.18
  4898.5 2075.09  4963.6 2074.53  4979.9 2074.48  4985.6 2072.78  4992.3 2072.43
  4992.5 2071.93  4996.3 2072.43  5005.9 2072.64  5009.6 2074.43  5015.3 2075.45
  5025.3 2076.09  5111.9 2077.19  5135.4 2078.70  5155.4 2082.46  5205.5 2083.08
  5295.5 2090.95  5325.5 2094.64  5369.9 2096.37  5385.6 2096.28  5432.2 2099.88
#Mann=7,-1,0
  4673.4    0.16       0  4898.5    0.07       0  4963.6    0.16       0
  4992.3    0.07       0  4996.3    0.16       0  5111.9    0.07       0
  5369.9   0.035       0
Bank Sta=4992.3,4996.3
Exp/Cntr=0.3,0.1

Type RM Length L Ch R = 1,2716,108,108,108
BEGIN DESCRIPTION:
Elm 67 2716.16
END DESCRIPTION:
XS GIS Cut Line= 3
      1525046.16      6768292.57      1525304.84      6768448.82
      1525676.35      6768502.64
#Sta/Elev= 30
  4702.5 2087.21  4726.5 2084.27  4736.2 2086.34  4742.0 2084.33  4757.5 2086.82
  4763.4 2084.91  4778.9 2084.93  4784.7 2081.41  4794.4 2080.05  4800.2 2075.50
  4806.3 2074.88  4911.6 2074.12  4975.1 2073.61  4990.4 2071.62  4996.2 2068.88
  4999.9 2068.76  5000.1 2068.26  5003.9 2068.76  5037.0 2075.44  5045.3 2076.21
  5095.8 2079.12  5102.2 2078.56  5107.3 2079.78  5136.2 2079.95  5146.3 2078.24
  5166.5 2078.01  5191.9 2081.91  5227.2 2085.01  5313.0 2086.70  5380.1 2089.62
#Mann=6,-1,0
  4702.5    0.16       0  4911.6    0.07       0  4975.1    0.16       0
  4999.9    0.07       0  5003.9    0.16       0  5191.9    0.07       0
Bank Sta=4999.9,5003.9
Exp/Cntr=0.3,0.1

Type RM Length L Ch R = 1,2608,81,81,81
BEGIN DESCRIPTION:
Elm 67 2608.37
END DESCRIPTION:
XS GIS Cut Line= 3
      1525002.74      6768431.46      1525247.55      6768535.63
      1525620.40      6768544.30
#Sta/Elev= 30
  4731.8 2083.68  4737.7 2082.56  4755.9 2081.84  4785.0 2076.48  4790.4 2077.13
  4808.6 2074.85  4814.1 2075.67  4832.1 2073.69  4837.7 2072.45  4843.1 2071.86
  4861.3 2072.37  4898.5 2071.99  5005.3 2071.74  5015.3 2070.82  5026.9 2068.45
  5033.3 2067.67  5033.6 2067.17  5037.1 2067.17  5037.3 2067.67  5045.3 2071.20
  5085.3 2076.49  5145.3 2080.41  5252.0 2082.80  5265.4 2083.05  5275.4 2083.75
  5295.4 2083.34  5305.4 2083.77  5335.4 2083.84  5365.4 2084.87  5370.8 2085.46
#Mann=6,-1,0
  4731.8    0.16       0  4898.5    0.07       0  5026.9    0.16       0
  5033.3    0.07       0  5037.3    0.16       0  5252.0    0.07       0
Bank Sta=5033.3,5037.3
Exp/Cntr=0.3,0.1

Type RM Length L Ch R = 1,2527,117,117,117
BEGIN DESCRIPTION:
Elm 67 2527.49
END DESCRIPTION:
XS GIS Cut Line= 3
      1524971.48      6768539.10      1525202.41      6768601.60
      1525615.57      6768603.34
#Sta/Elev= 30
  4757.5 2075.63  4769.4 2075.98  4792.2 2074.99  4802.6 2075.73  4809.2 2077.54
  4814.4 2076.46  4823.3 2078.13  4833.7 2079.24  4843.9 2077.15  4854.4 2072.67
  4889.0 2071.42  4947.6 2071.22  4963.5 2070.53  4978.7 2070.96  4995.5 2069.97
  5029.3 2070.73  5069.1 2070.85  5089.3 2070.45  5097.3 2069.04  5097.6 2068.54
  5101.1 2068.54  5101.3 2069.04  5139.3 2073.49  5179.3 2076.10  5209.3 2078.81
  5249.3 2080.06  5315.9 2080.40  5379.3 2080.71  5389.3 2081.45  5409.9 2081.50
#Mann=5,-1,0
  4757.5    0.07       0  5069.1    0.16       0  5097.3    0.07       0
  5101.3    0.16       0  5315.9    0.07       0
Bank Sta=5097.3,5101.3
Exp/Cntr=0.3,0.1

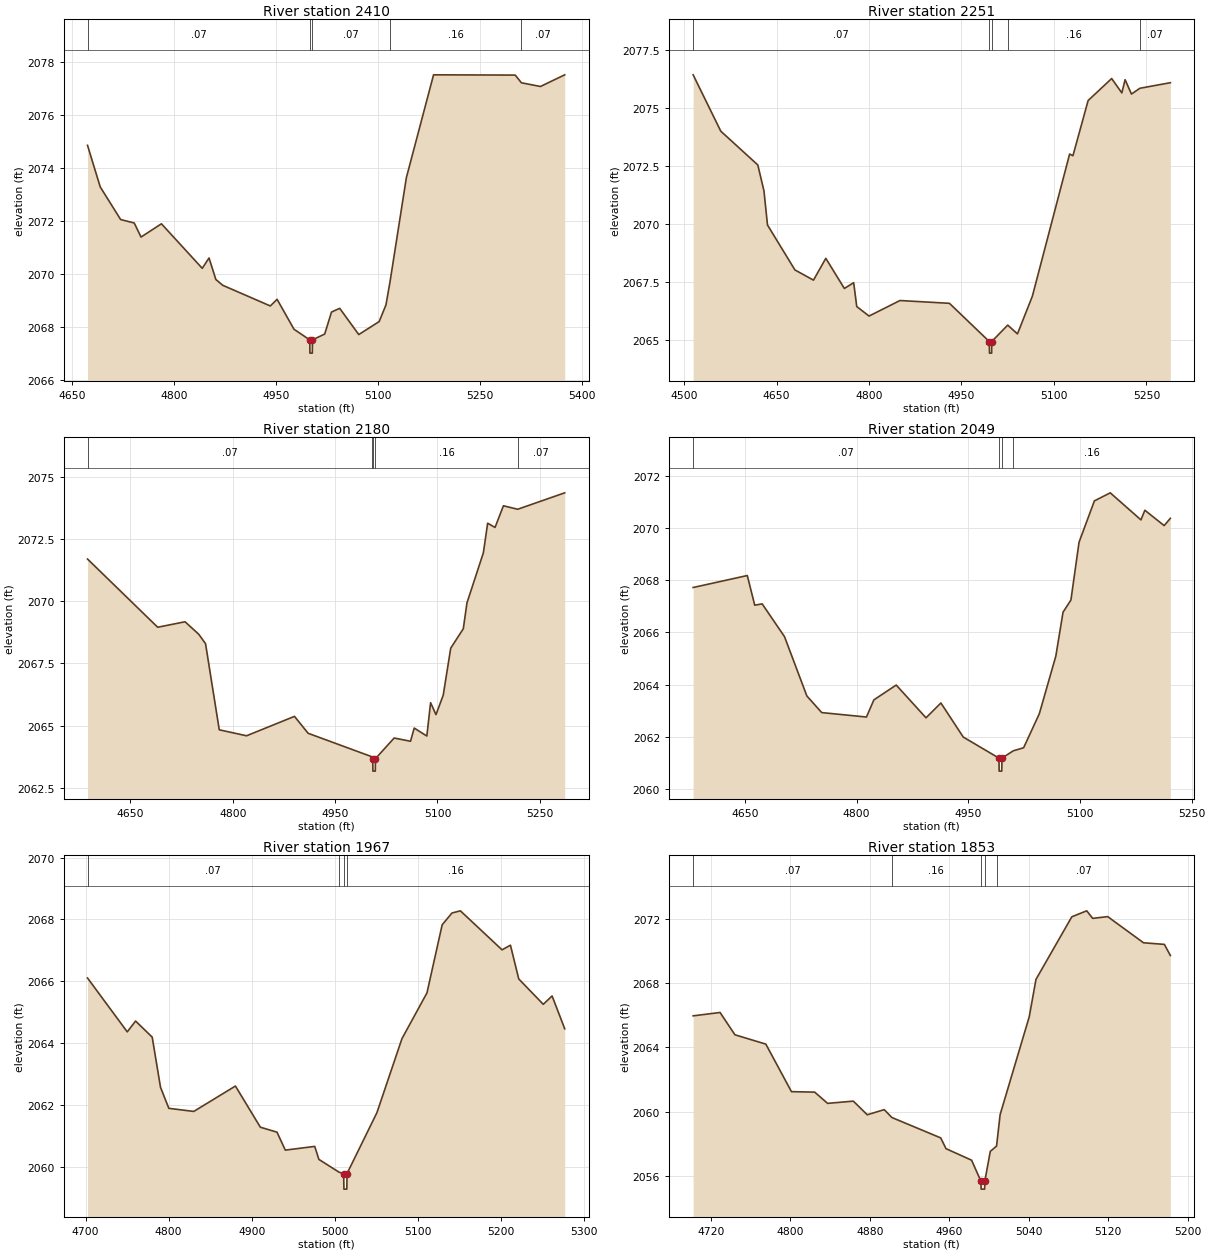
Type RM Length L Ch R = 1,2410,159,159,159
BEGIN DESCRIPTION:
Elm 67 2409.92
END DESCRIPTION:
XS GIS Cut Line= 3
      1524926.34      6768693.62      1525263.17      6768704.03
      1525627.78      6768691.88
#Sta/Elev= 30
  4673.2 2074.84  4691.9 2073.27  4721.9 2072.04  4741.9 2071.91  4751.9 2071.38
  4781.9 2071.88  4841.9 2070.20  4851.9 2070.59  4861.9 2069.78  4872.0 2069.56
  4942.0 2068.78  4952.0 2069.03  4976.9 2067.90  5000.0 2067.50  5000.3 2067.00
  5003.8 2067.00  5004.0 2067.50  5022.0 2067.72  5032.0 2068.55  5044.1 2068.69
  5072.1 2067.70  5102.1 2068.19  5112.1 2068.82  5118.0 2069.68  5142.1 2073.62
  5182.1 2077.50  5302.2 2077.49  5311.3 2077.20  5339.3 2077.06  5375.0 2077.50
#Mann=5,-1,0
  4673.2    0.07       0  5000.0    0.07       0  5004.0    0.07       0
  5118.0    0.16       0  5311.3    0.07       0
Bank Sta=5000,5004
Exp/Cntr=0.3,0.1

Type RM Length L Ch R = 1,2251,71,71,71
BEGIN DESCRIPTION:
Elm 67 2250.81
END DESCRIPTION:
XS GIS Cut Line= 3
      1524860.35      6768794.31      1525343.03      6768829.03
      1525613.86      6768724.87
#Sta/Elev= 30
  4514.7 2076.45  4559.5 2074.02  4619.6 2072.56  4629.6 2071.44  4635.3 2069.97
  4679.8 2068.03  4709.9 2067.59  4729.9 2068.53  4760.0 2067.23  4775.1 2067.48
  4780.1 2066.45  4800.1 2066.04  4850.2 2066.71  4930.4 2066.59  4995.1 2064.94
  4995.4 2064.44  4998.9 2064.44  4999.1 2064.94  5025.0 2065.65  5040.8 2065.27
  5065.0 2066.90  5125.4 2073.03  5130.8 2072.96  5155.4 2075.34  5193.6 2076.29
  5210.1 2075.67  5215.4 2076.24  5225.7 2075.62  5239.4 2075.87  5288.8 2076.11
#Mann=5,-1,0
  4514.7    0.07       0  4995.1    0.07       0  4999.1    0.07       0
  5025.0    0.16       0  5239.4    0.07       0
Bank Sta=4995.1,4999.1
Exp/Cntr=0.3,0.1

Type RM Length L Ch R = 1,2180,131,131,131
BEGIN DESCRIPTION:
Elm 67 2180.18
END DESCRIPTION:
XS GIS Cut Line= 3
      1524952.41      6768921.05      1525367.34      6768895.00
      1525629.46      6768787.38
#Sta/Elev= 30
  4587.3 2071.69  4690.1 2068.95  4730.2 2069.17  4750.2 2068.67  4760.2 2068.29
  4780.3 2064.83  4820.3 2064.59  4890.5 2065.37  4910.5 2064.69  5004.7 2063.74
  5005.1 2063.67  5005.4 2063.17  5008.9 2063.17  5009.1 2063.67  5036.5 2064.50
  5060.5 2064.37  5065.9 2064.90  5084.4 2064.58  5089.9 2065.92  5097.8 2065.44
  5108.4 2066.22  5119.4 2068.11  5137.8 2068.89  5143.2 2069.93  5167.2 2071.94
  5173.5 2073.13  5184.3 2072.96  5196.6 2073.83  5217.5 2073.69  5286.4 2074.35
#Mann=5,-1,0
  4587.3    0.07       0  5004.7    0.16       0  5005.1    0.07       0
  5009.1    0.16       0  5217.5    0.07       0
Bank Sta=5005.1,5009.1
Exp/Cntr=0.3,0.1

Type RM Length L Ch R = 1,2049,82,82,82
BEGIN DESCRIPTION:
Elm 67 2048.81
END DESCRIPTION:
XS GIS Cut Line= 3
      1525032.31      6768990.49      1525455.88      6768992.23
      1525661.26      6768921.47
#Sta/Elev= 30
  4580.5 2067.73  4653.2 2068.19  4663.2 2067.05  4673.2 2067.10  4703.2 2065.84
  4733.2 2063.56  4753.2 2062.92  4813.2 2062.75  4823.2 2063.41  4853.2 2063.98
  4893.2 2062.72  4913.2 2063.29  4943.2 2061.98  4991.2 2061.17  4991.4 2060.67
  4994.9 2060.67  4995.2 2061.17  5010.3 2061.45  5024.3 2061.57  5045.4 2062.88
  5067.5 2065.09  5077.2 2066.78  5087.8 2067.25  5098.7 2069.47  5119.3 2071.06
  5140.6 2071.37  5181.8 2070.33  5187.1 2070.70  5213.0 2070.11  5221.3 2070.39
#Mann=4,-1,0
  4580.5    0.07       0  4991.2    0.07       0  4995.2    0.07       0
  5010.3    0.16       0
Bank Sta=4991.2,4995.2
Exp/Cntr=0.3,0.1

Type RM Length L Ch R = 1,1967,114,114,114
BEGIN DESCRIPTION:
Elm 67 1966.88
END DESCRIPTION:
XS GIS Cut Line= 3
      1525157.23      6769063.41      1525454.14      6769073.82
      1525730.13      6769051.26
#Sta/Elev= 30
  4702.4 2066.11  4750.2 2064.37  4760.2 2064.72  4780.2 2064.20  4790.2 2062.58
  4800.2 2061.90  4830.2 2061.80  4880.3 2062.62  4910.3 2061.29  4930.3 2061.13
  4940.3 2060.55  4975.7 2060.67  4980.7 2060.25  5004.8 2059.84  5010.5 2059.79
  5010.8 2059.29  5014.3 2059.29  5014.5 2059.79  5050.5 2061.76  5080.6 2064.15
  5110.7 2065.63  5129.0 2067.83  5140.8 2068.21  5150.9 2068.28  5201.0 2067.02
  5211.1 2067.17  5221.1 2066.08  5250.6 2065.26  5261.2 2065.53  5276.4 2064.47
#Mann=4,-1,0
  4702.4    0.07       0  5004.8    0.16       0  5010.5    0.07       0
  5014.5    0.16       0
Bank Sta=5010.5,5014.5
Exp/Cntr=0.3,0.1

Type RM Length L Ch R = 1,1853,136,136,136
BEGIN DESCRIPTION:
Elm 67 1852.91
END DESCRIPTION:
XS GIS Cut Line= 3
      1525169.43      6769089.45      1525454.14      6769188.41
      1525603.41      6769287.34
#Sta/Elev= 30
  4702.0 2065.97  4729.1 2066.18  4744.1 2064.79  4775.2 2064.21  4801.0 2061.25
  4824.4 2061.22  4837.4 2060.52  4863.3 2060.66  4877.3 2059.81  4894.4 2060.13
  4902.1 2059.64  4951.3 2058.37  4956.6 2057.70  4982.4 2056.98  4991.7 2055.68
  4992.0 2055.18  4995.5 2055.18  4995.7 2055.68  5001.2 2057.53  5007.5 2057.86
  5011.1 2059.82  5040.4 2065.91  5047.2 2068.24  5083.3 2072.14  5098.3 2072.51
  5104.3 2072.04  5119.4 2072.15  5155.5 2070.52  5176.5 2070.42  5182.5 2069.73
#Mann=5,-1,0
  4702.0    0.07       0  4902.1    0.16       0  4991.7    0.07       0
  4995.7    0.16       0  5007.5    0.07       0
Bank Sta=4991.7,4995.7
Exp/Cntr=0.3,0.1

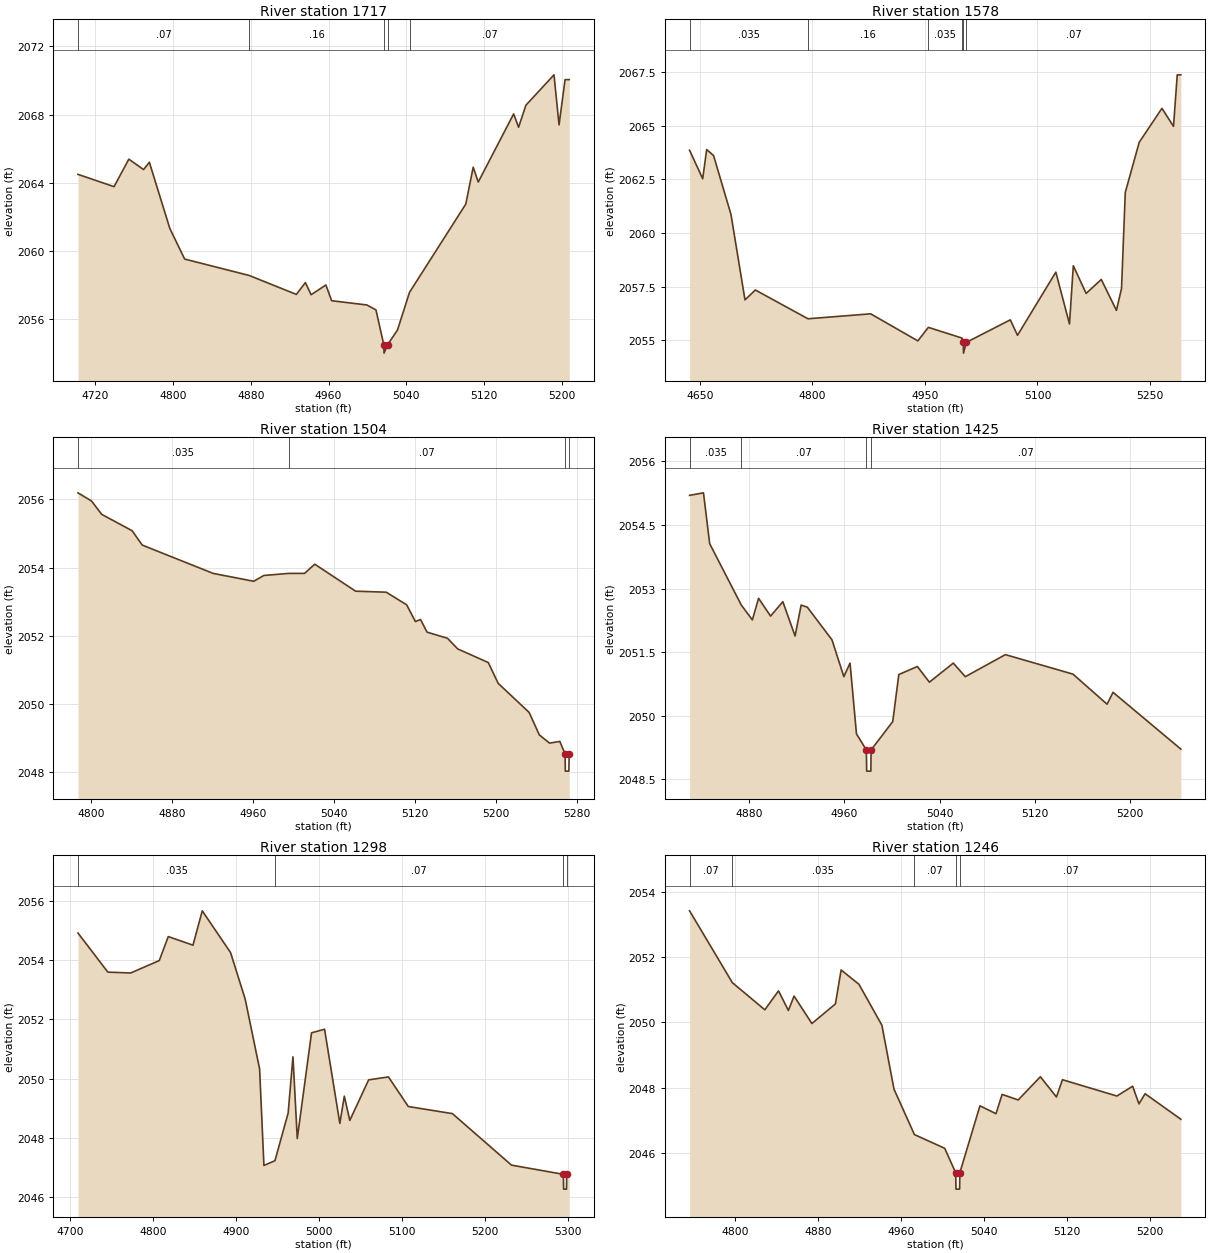
Type RM Length L Ch R = 1,1717,139,139,139
BEGIN DESCRIPTION:
Elm 67 1717.05
END DESCRIPTION:
XS GIS Cut Line= 3
      1525106.88      6769124.15      1525360.39      6769287.37
      1525558.30      6769335.98
#Sta/Elev= 30
  4702.3 2064.50  4739.4 2063.78  4754.6 2065.39  4769.8 2064.78  4775.7 2065.21
  4796.8 2061.33  4812.0 2059.54  4878.3 2058.58  4926.9 2057.47  4936.2 2058.16
  4942.1 2057.45  4957.3 2058.02  4963.2 2057.10  4999.5 2056.85  5008.8 2056.56
  5016.8 2054.53  5017.1 2054.03  5020.8 2054.53  5030.9 2055.38  5043.3 2057.59
  5101.2 2062.76  5108.8 2064.92  5114.0 2064.05  5150.4 2068.04  5155.5 2067.26
  5163.0 2068.55  5191.9 2070.33  5197.1 2067.40  5203.3 2070.05  5207.6 2070.05
#Mann=5,-1,0
  4702.3    0.07       0  4878.3    0.16       0  5016.8    0.07       0
  5020.8    0.16       0  5043.3    0.07       0
Bank Sta=5016.8,5020.8
Exp/Cntr=0.3,0.1

Type RM Length L Ch R = 1,1578,74,74,74
BEGIN DESCRIPTION:
Elm 67 1577.61
END DESCRIPTION:
XS GIS Cut Line= 3
      1525004.50      6769287.37      1525348.24      6769395.00
      1525639.93      6769351.60
#Sta/Elev= 30
  4636.1 2063.86  4653.6 2062.53  4658.9 2063.89  4668.1 2063.61  4691.3 2060.87
  4710.0 2056.89  4723.8 2057.35  4794.0 2056.01  4877.6 2056.24  4940.5 2054.98
  4954.5 2055.61  4999.5 2055.11  5001.1 2054.91  5001.4 2054.41  5005.1 2054.91
  5063.8 2055.96  5073.4 2055.24  5124.5 2058.18  5142.7 2055.77  5147.8 2058.48
  5164.9 2057.19  5185.1 2057.84  5205.3 2056.40  5212.1 2057.42  5217.1 2061.89
  5235.7 2064.23  5266.0 2065.81  5281.4 2064.97  5286.4 2067.37  5291.2 2067.37
#Mann=6,-1,0
  4636.1   0.035       0  4794.0    0.16       0  4954.5   0.035       0
  4999.5    0.07       0  5001.1    0.07       0  5005.1    0.07       0
Bank Sta=5001.1,5005.1
Exp/Cntr=0.3,0.1

Type RM Length L Ch R = 1,1504,79,79,79
BEGIN DESCRIPTION:
Elm 67 1503.72
END DESCRIPTION:
XS GIS Cut Line= 3
      1525141.60      6769471.39      1525353.45      6769467.92
      1525624.27      6769500.91
#Sta/Elev= 30
  4787.3 2056.19  4800.7 2055.95  4810.7 2055.56  4840.7 2055.08  4850.7 2054.66
  4920.7 2053.83  4960.7 2053.60  4970.7 2053.77  4995.1 2053.83  5010.8 2053.83
  5020.9 2054.10  5061.2 2053.31  5091.4 2053.28  5111.6 2052.91  5120.2 2052.42
  5125.3 2052.48  5131.7 2052.11  5151.9 2051.93  5161.9 2051.62  5192.1 2051.22
  5201.9 2050.61  5232.4 2049.76  5242.5 2049.10  5252.6 2048.86  5262.7 2048.91
  5267.9 2048.54  5268.1 2048.04  5271.6 2048.04  5271.9 2048.54  5272.0 2048.54
#Mann=4,-1,0
  4787.3   0.035       0  4995.1    0.07       0  5267.9    0.07       0
  5271.9    0.07       0
Bank Sta=5267.9,5271.9
Exp/Cntr=0.3,0.1

Type RM Length L Ch R = 1,1425,127,127,127
BEGIN DESCRIPTION:
Elm 67 1425.31
END DESCRIPTION:
XS GIS Cut Line= 3
      1525198.97      6769585.97      1525370.81      6769542.57
      1525605.14      6769516.54
#Sta/Elev= 30
  4829.8 2055.20  4841.5 2055.26  4846.7 2054.06  4873.3 2052.61  4882.6 2052.26
  4887.8 2052.77  4897.9 2052.35  4908.2 2052.69  4918.5 2051.88  4923.6 2052.61
  4928.8 2052.56  4949.5 2051.79  4959.5 2050.92  4964.7 2051.24  4970.1 2049.57
  4978.4 2049.19  4978.7 2048.69  4982.2 2048.69  4982.4 2049.19  5000.6 2049.86
  5005.7 2050.97  5021.3 2051.16  5031.4 2050.79  5051.5 2051.24  5061.6 2050.92
  5095.3 2051.44  5152.1 2050.98  5180.8 2050.27  5185.8 2050.55  5242.8 2049.21
#Mann=4,-1,0
  4829.8   0.035       0  4873.3    0.07       0  4978.4    0.07       0
  4982.4    0.07       0
Bank Sta=4978.4,4982.4
Exp/Cntr=0.3,0.1

Type RM Length L Ch R = 1,1298,52,52,52
BEGIN DESCRIPTION:
Elm 67 1297.87
END DESCRIPTION:
XS GIS Cut Line= 3
      1525190.25      6769679.73      1525464.56      6769606.81
      1525749.31      6769488.74
#Sta/Elev= 30
  4709.3 2054.92  4745.3 2053.60  4772.8 2053.57  4807.3 2053.99  4818.1 2054.80
  4847.9 2054.51  4859.1 2055.67  4893.2 2054.26  4910.8 2052.69  4928.2 2050.33
  4933.4 2047.07  4946.7 2047.23  4962.6 2048.84  4968.4 2050.74  4973.6 2047.98
  4990.8 2051.55  5006.5 2051.67  5024.9 2048.49  5030.3 2049.41  5036.9 2048.59
  5059.6 2049.96  5083.5 2050.06  5107.4 2049.06  5160.6 2048.82  5231.8 2047.08
  5294.3 2046.77  5294.6 2046.27  5298.1 2046.27  5298.3 2046.77  5301.4 2046.77
#Mann=4,-1,0
  4709.3   0.035       0  4946.7    0.07       0  5294.3    0.07       0
  5298.3    0.07       0
Bank Sta=5294.3,5298.3
Exp/Cntr=0.3,0.1

Type RM Length L Ch R = 1,1246,71,71,71
BEGIN DESCRIPTION:
Elm 67 1245.98
END DESCRIPTION:
XS GIS Cut Line= 3
      1525287.50      6769745.69      1525509.70      6769639.80
      1525704.85      6769522.36
#Sta/Elev= 30
  4756.1 2053.41  4797.4 2051.21  4828.7 2050.38  4841.9 2050.96  4851.4 2050.36
  4856.9 2050.80  4874.1 2049.96  4896.8 2050.56  4902.3 2051.60  4919.5 2051.16
  4941.6 2049.91  4953.3 2047.95  4973.0 2046.56  5002.2 2046.14  5012.8 2045.39
  5013.1 2044.89  5016.6 2044.89  5016.8 2045.39  5036.2 2047.44  5051.7 2047.20
  5057.6 2047.79  5073.1 2047.62  5094.5 2048.33  5110.0 2047.71  5115.8 2048.24
  5168.3 2047.74  5183.5 2048.04  5189.6 2047.50  5195.5 2047.81  5230.0 2047.03
#Mann=5,-1,0
  4756.1    0.07       0  4797.4   0.035       0  4973.0    0.07       0
  5012.8    0.07       0  5016.8    0.07       0
Bank Sta=5012.8,5016.8
Exp/Cntr=0.3,0.1

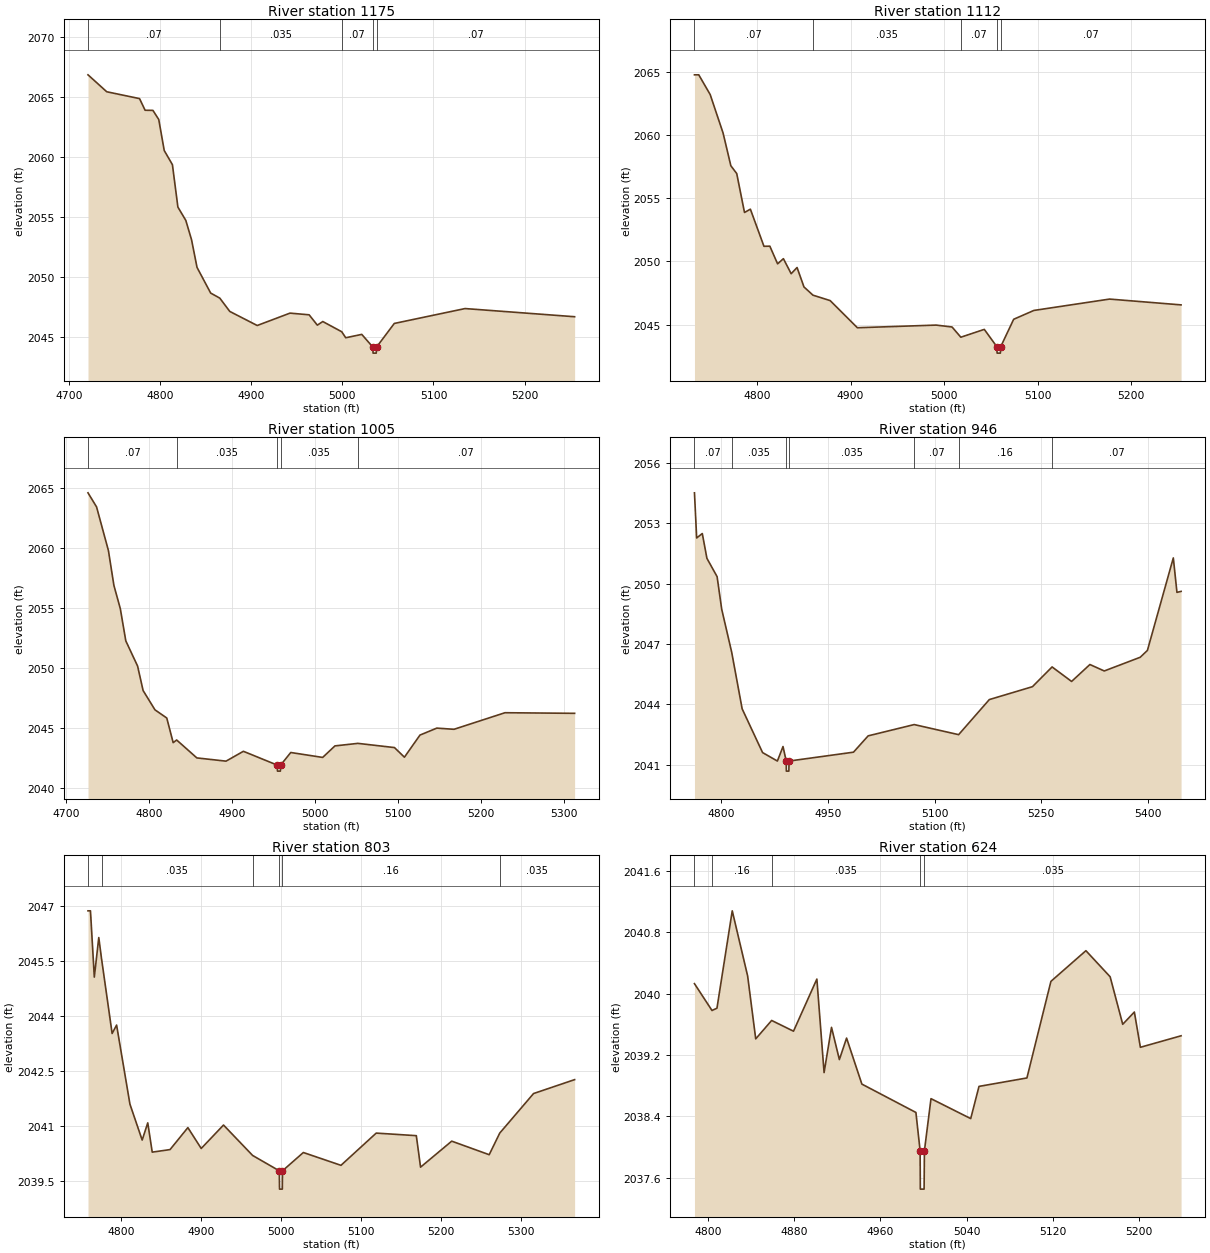
Type RM Length L Ch R = 1,1175,63,63,63
BEGIN DESCRIPTION:
Elm 67 1174.95
END DESCRIPTION:
XS GIS Cut Line= 3
      1525325.71      6769846.37      1525561.78      6769688.41
      1525730.81      6769503.86
#Sta/Elev= 30
  4720.7 2066.85  4741.3 2065.44  4777.3 2064.87  4783.4 2063.90  4792.0 2063.89
  4798.4 2063.13  4804.4 2060.55  4813.4 2059.37  4819.4 2055.84  4828.1 2054.73
  4834.4 2053.12  4840.4 2050.82  4855.4 2048.68  4865.4 2048.26  4876.4 2047.15
  4906.5 2045.98  4942.5 2047.01  4963.5 2046.87  4972.5 2046.01  4978.5 2046.31
  4999.3 2045.46  5003.7 2044.96  5021.3 2045.24  5033.5 2044.18  5033.7 2043.68
  5037.2 2043.68  5037.5 2044.18  5057.0 2046.15  5134.7 2047.39  5255.0 2046.71
#Mann=5,-1,0
  4720.7    0.07       0  4865.4   0.035       0  4999.3    0.07       0
  5033.5    0.07       0  5037.5    0.07       0
Bank Sta=5033.5,5037.5
Exp/Cntr=0.3,0.1

Type RM Length L Ch R = 1,1112,107,107,107
BEGIN DESCRIPTION:
Elm 67 1112.29
END DESCRIPTION:
XS GIS Cut Line= 3
      1525391.61      6769898.50      1525598.24      6769742.23
      1525726.72      6769514.78
#Sta/Elev= 30
  4733.1 2064.78  4737.7 2064.78  4749.9 2063.22  4763.7 2060.17  4772.0 2057.58
  4778.3 2056.96  4786.6 2053.88  4792.9 2054.14  4807.4 2051.20  4813.7 2051.21
  4822.0 2049.81  4828.2 2050.22  4836.5 2049.03  4842.8 2049.52  4850.2 2047.98
  4859.8 2047.33  4878.2 2046.90  4907.3 2044.75  4991.5 2044.96  5008.5 2044.81
  5017.9 2044.00  5043.0 2044.62  5056.5 2043.24  5056.7 2042.74  5060.2 2042.74
  5060.5 2043.24  5074.4 2045.42  5096.0 2046.12  5176.9 2047.02  5253.4 2046.56
#Mann=5,-1,0
  4733.1    0.07       0  4859.8   0.035       0  5017.9    0.07       0
  5056.5   0.035       0  5060.5    0.07       0
Bank Sta=5056.5,5060.5
Exp/Cntr=0.3,0.1

Type RM Length L Ch R = 1,1005,59,59,59
BEGIN DESCRIPTION:
Elm 67 1004.91
END DESCRIPTION:
XS GIS Cut Line= 3
      1525475.01      6769992.20      1525676.37      6769818.62
      1525744.08      6769506.11
#Sta/Elev= 30
  4726.8 2064.60  4737.1 2063.43  4751.4 2059.79  4758.0 2056.89  4765.7 2054.96
  4772.3 2052.28  4786.5 2050.18  4793.1 2048.15  4807.4 2046.54  4821.6 2045.86
  4829.3 2043.81  4833.5 2044.03  4857.8 2042.54  4892.9 2042.27  4913.8 2043.09
  4954.6 2041.94  4954.8 2041.44  4958.3 2041.44  4958.6 2041.94  4970.8 2042.99
  5009.2 2042.58  5024.0 2043.54  5051.6 2043.75  5095.6 2043.40  5107.6 2042.60
  5126.3 2044.44  5146.6 2045.02  5167.2 2044.92  5228.6 2046.30  5312.4 2046.25
#Mann=5,-1,0
  4726.8    0.07       0  4833.5   0.035       0  4954.6   0.035       0
  4958.6   0.035       0  5051.6    0.07       0
Bank Sta=4954.6,4958.6
Exp/Cntr=0.3,0.1

Type RM Length L Ch R = 1,946,143,143,143
BEGIN DESCRIPTION:
Elm 67 945.958
END DESCRIPTION:
XS GIS Cut Line= 3
      1525568.92      6770036.53      1525719.56      6769853.17
      1525781.36      6769411.17
#Sta/Elev= 30
  4762.7 2054.50  4765.8 2052.26  4773.7 2052.48  4780.2 2051.25  4794.5 2050.34
  4801.0 2048.72  4815.0 2046.59  4829.7 2043.78  4858.4 2041.61  4879.2 2041.19
  4887.1 2041.91  4891.6 2041.19  4891.8 2040.69  4895.3 2040.69  4895.6 2041.19
  4986.1 2041.63  5006.7 2042.44  5071.4 2043.00  5133.8 2042.50  5176.9 2044.24
  5237.5 2044.88  5265.1 2045.86  5292.5 2045.14  5318.2 2045.98  5338.4 2045.66
  5388.9 2046.34  5399.0 2046.68  5435.4 2051.27  5440.5 2049.56  5446.3 2049.61
#Mann=7,-1,0
  4762.7    0.07       0  4815.0   0.035       0  4891.6   0.035       0
  4895.6   0.035       0  5071.4    0.07       0  5133.8    0.16       0
  5265.1    0.07       0
Bank Sta=4891.6,4895.6
Exp/Cntr=0.3,0.1

Type RM Length L Ch R = 1,803,179,179,179
BEGIN DESCRIPTION:
Elm 67 4549
END DESCRIPTION:
XS GIS Cut Line= 3
      1525614.50      6770047.36      1525830.00      6769938.58
      1525957.41      6769593.77
#Sta/Elev= 30
  4758.6 2046.88  4761.7 2046.88  4766.5 2045.07  4772.1 2046.15  4775.5 2045.58
  4788.8 2043.53  4794.4 2043.76  4811.1 2041.60  4826.4 2040.62  4833.4 2041.09
  4839.0 2040.29  4861.3 2040.36  4883.6 2040.96  4900.3 2040.39  4928.2 2041.03
  4964.6 2040.20  4998.0 2039.78  4998.3 2039.28  5001.8 2039.28  5002.0 2039.78
  5028.1 2040.28  5075.2 2039.93  5119.3 2040.81  5169.5 2040.74  5174.8 2039.88
  5213.8 2040.59  5260.7 2040.22  5273.9 2040.81  5316.2 2041.89  5367.6 2042.27
#Mann=6,-1,0
  4758.6    0.07       0  4775.5   0.035       0  4964.6    0.16       0
  4998.0    0.07       0  5002.0    0.16       0  5273.9   0.035       0
Bank Sta=4998,5002
Exp/Cntr=0.3,0.1

Type RM Length L Ch R = 1,624,126,126,126
BEGIN DESCRIPTION:
Elm 67 4548
END DESCRIPTION:
XS GIS Cut Line= 3
      1525829.98      6770013.02      1525971.65      6769854.23
      1526076.76      6769639.36
#Sta/Elev= 30
  4787.2 2040.13  4803.5 2039.78  4808.1 2039.81  4822.3 2041.08  4836.6 2040.23
  4844.1 2039.41  4858.9 2039.65  4879.2 2039.51  4900.9 2040.19  4907.6 2038.97
  4914.5 2039.56  4921.8 2039.14  4928.5 2039.42  4942.7 2038.82  4992.9 2038.45
  4996.8 2037.95  4997.0 2037.45  5000.5 2037.45  5000.8 2037.95  5006.9 2038.63
  5043.8 2038.37  5051.5 2038.79  5096.0 2038.90  5118.3 2040.16  5150.8 2040.56
  5173.3 2040.22  5185.0 2039.60  5195.8 2039.76  5201.4 2039.30  5239.2 2039.45
#Mann=5,-1,0
  4787.2   0.035       0  4803.5    0.16       0  4858.9   0.035       0
  4996.8   0.035       0  5000.8   0.035       0
Bank Sta=4996.8,5000.8
Exp/Cntr=0.3,0.1

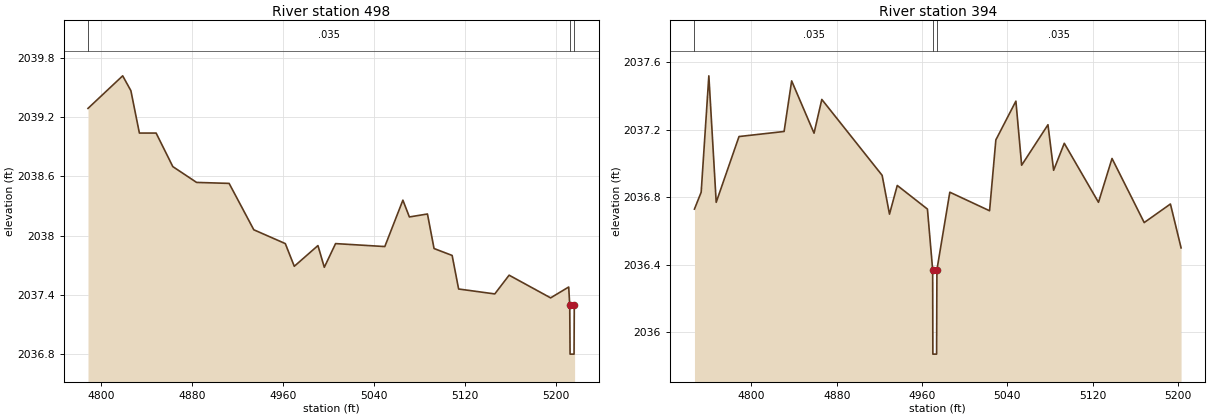
Type RM Length L Ch R = 1,498,104,104,104
BEGIN DESCRIPTION:
Elm 67 4547
END DESCRIPTION:
XS GIS Cut Line= 3
      1525894.49      6770060.35      1526065.64      6769936.44
      1526172.24      6769747.88
#Sta/Elev= 30
  4788.7 2039.29  4819.2 2039.62  4826.4 2039.47  4833.9 2039.04  4848.6 2039.04
  4863.3 2038.70  4884.2 2038.54  4912.8 2038.53  4934.5 2038.06  4962.2 2037.92
  4970.1 2037.69  4990.9 2037.90  4996.5 2037.68  5006.4 2037.92  5049.7 2037.89
  5065.6 2038.36  5071.3 2038.19  5087.2 2038.22  5093.0 2037.87  5108.9 2037.80
  5114.6 2037.46  5146.4 2037.41  5159.0 2037.60  5195.5 2037.37  5211.4 2037.48
  5212.3 2037.30  5212.6 2036.80  5216.1 2036.80  5216.3 2037.30  5216.6 2037.30
#Mann=3,-1,0
  4788.7   0.035       0  5212.3   0.035       0  5216.3   0.035       0
Bank Sta=5212.3,5216.3
Exp/Cntr=0.3,0.1

Type RM Length L Ch R = 1,394,90,90,90
BEGIN DESCRIPTION:
Elm 67 4546
END DESCRIPTION:
XS GIS Cut Line= 3
      1525976.95      6770168.86      1526151.86      6769985.38
      1526224.32      6769795.64
#Sta/Elev= 30
  4746.5 2036.73  4752.8 2036.83  4760.0 2037.52  4766.9 2036.77  4788.3 2037.16
  4830.6 2037.19  4837.7 2037.49  4858.7 2037.18  4866.0 2037.38  4922.6 2036.93
  4929.5 2036.70  4936.8 2036.87  4965.1 2036.73  4970.0 2036.37  4970.2 2035.87
  4973.7 2035.87  4974.0 2036.37  4986.1 2036.83  5023.4 2036.72  5029.3 2037.14
  5048.1 2037.37  5053.5 2036.99  5078.2 2037.23  5083.5 2036.96  5093.5 2037.12
  5125.6 2036.77  5138.3 2037.03  5168.5 2036.65  5193.1 2036.76  5203.1 2036.50
#Mann=3,-1,0
  4746.5   0.035       0  4970.0   0.035       0  4974.0   0.035       0
Bank Sta=4970,4974
Exp/Cntr=0.3,0.1