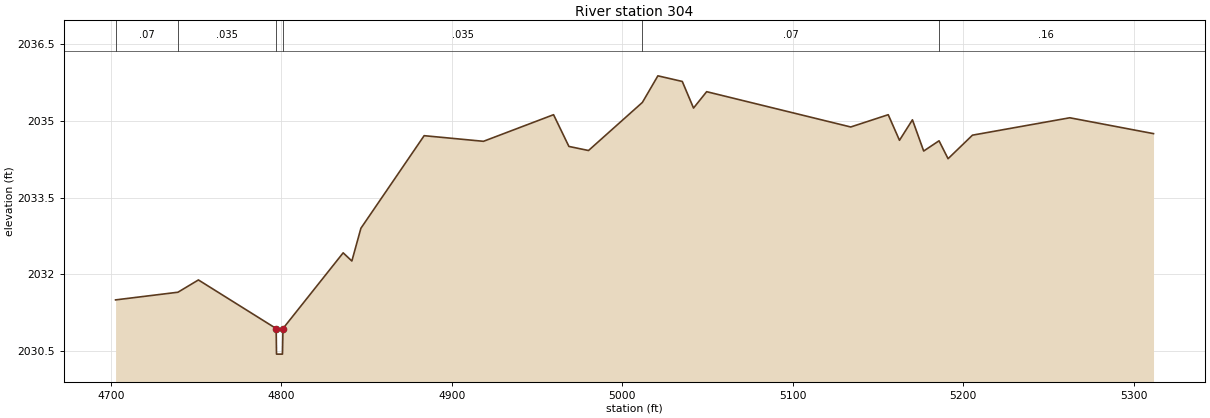
HEC-RAS study Elm 67.prj: Elm 67 Base Level Engineering

--- Elm 67.g01 (geometry) --- (continued)

Type RM Length L Ch R = 1,304,0,0,0
BEGIN DESCRIPTION:
Elm 67 4545
END DESCRIPTION:
XS GIS Cut Line= 3
      1526148.38      6770338.10      1526216.26      6770048.76
      1526418.71      6769811.89
#Sta/Elev= 30
  4702.8 2031.50  4739.4 2031.65  4751.4 2031.89  4797.0 2030.94  4797.2 2030.44
  4800.7 2030.44  4801.0 2030.94  4836.3 2032.42  4841.4 2032.26  4846.7 2032.90
  4883.8 2034.71  4918.6 2034.60  4959.7 2035.12  4968.7 2034.50  4980.2 2034.42
  5011.8 2035.36  5020.9 2035.88  5035.2 2035.77  5041.8 2035.25  5049.5 2035.57
  5134.0 2034.88  5156.0 2035.12  5162.6 2034.62  5170.2 2035.02  5176.8 2034.41
  5185.8 2034.61  5191.1 2034.26  5205.4 2034.72  5262.5 2035.06  5311.6 2034.75
#Mann=6,-1,0
  4702.8    0.07       0  4739.4   0.035       0  4797.0   0.035       0
  4801.0   0.035       0  5011.8    0.07       0  5185.8    0.16       0
Bank Sta=4797,4801
Exp/Cntr=0.3,0.1

Chan Stop Cuts=-1