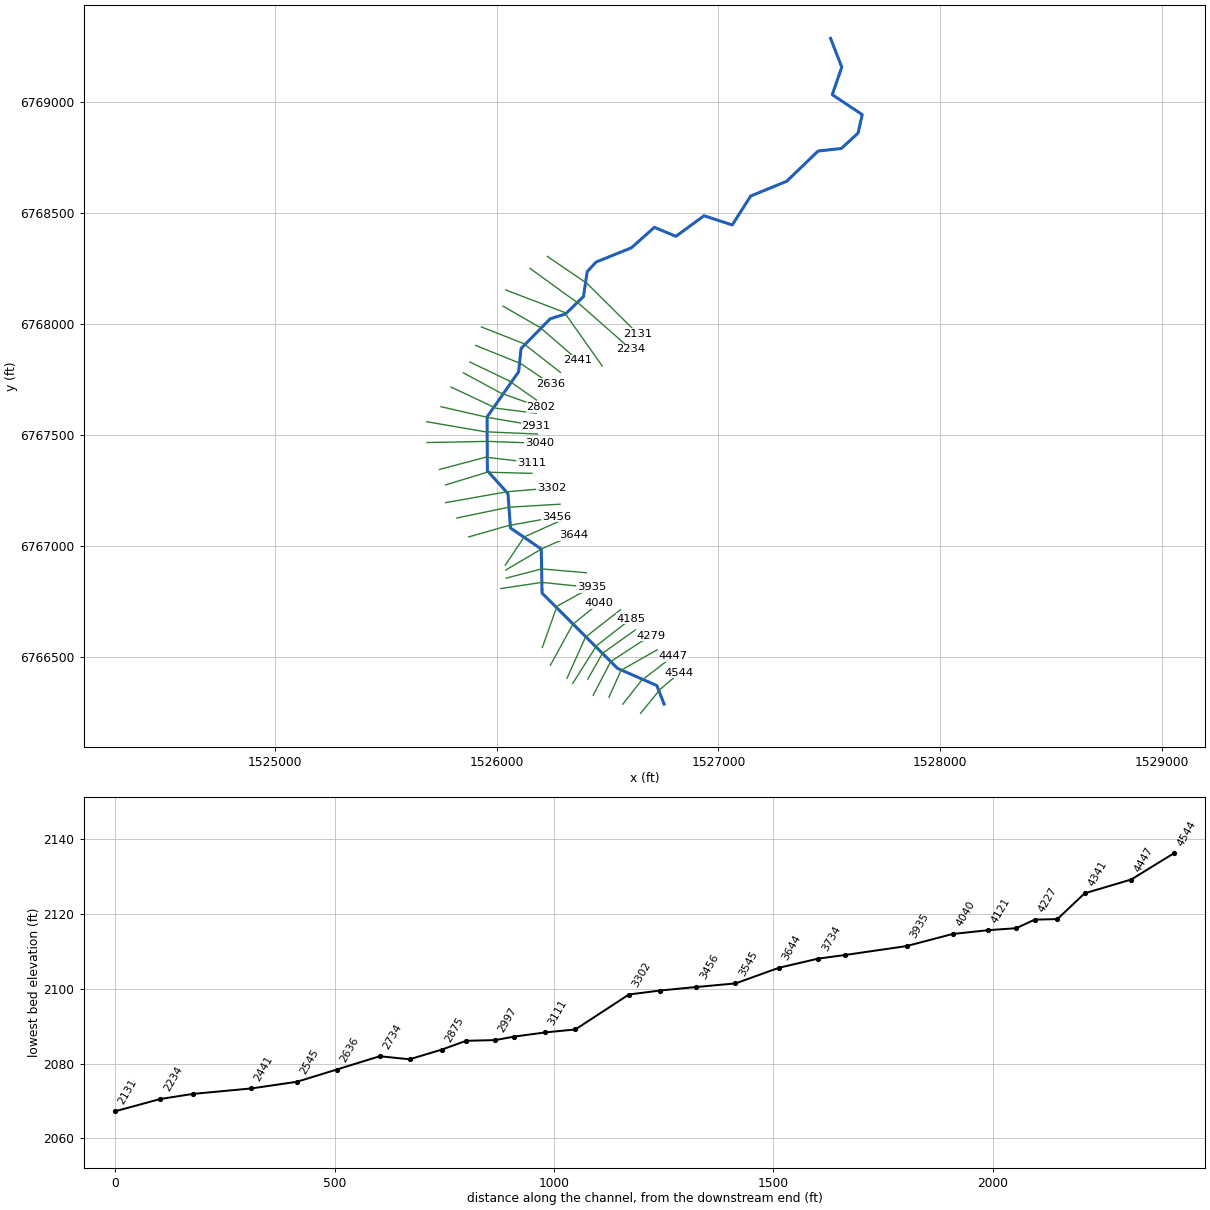
--- Elm 68.prj (project) ---

Proj Title=Elm 68 Base Level Engineering
Current Plan=p01
Default Exp/Contr=0.3,0.1
English Units
Geom File=g01
Flow File=f01
Plan File=p01
BEGIN DESCRIPTION:
Elm 68
END DESCRIPTION:

--- Elm 68.p01 (plan) ---

Plan Title=Multiple Run
Short Identifier=Multiple
Geom File=g01
Flow File=f01
Subcritical Flow
K Sum by GR= 0
Std Step Tol= 0.01
Critical Tol= 0.01
Num of Std Step Trials= 20
Max Error Tol= 0.3
Flow Tol Ratio= 0.001
Split Flow NTrial= 30
Split Flow Tol= 0.02
Split Flow Ratio= 0.02
Log Output Level= 0
Friction Slope Method= 1
Unsteady Friction Slope Method= 2
Unsteady Bridges Friction Slope Method= 1
Parabolic Critical Depth
Global Vel Dist=  1 , 1 , 1
Global Log Level= 0
CheckData=True
Encroach Param= -1, 0, 0, 0
BEGIN DESCRIPTION:
Multiple Run
END DESCRIPTION:

--- Elm 68.f01 (steady flow) ---

Flow Title=Multiple
Number of Profiles=7
Profile Names=10-year,25-year,50-year,1pct_min,100-year,1pct_plu,500-year
River Rch & RM= Elm 68,Reach-1,4544
      92     123     147     110     177     243     257
River Rch & RM= Elm 68,Reach-1,3794
     158     216     264     202     323     445     488
Boundary for River Rch & Prof#=Elm 68,Reach-1,1
Up Type=0
Dn Type=3
Dn Slope=0.005
Boundary for River Rch & Prof#=Elm 68,Reach-1,2
Up Type=0
Dn Type=3
Dn Slope=0.005
Boundary for River Rch & Prof#=Elm 68,Reach-1,3
Up Type=0
Dn Type=3
Dn Slope=0.005
Boundary for River Rch & Prof#=Elm 68,Reach-1,4
Up Type=0
Dn Type=3
Dn Slope=0.005
Boundary for River Rch & Prof#=Elm 68,Reach-1,5
Up Type=0
Dn Type=3
Dn Slope=0.005
Boundary for River Rch & Prof#=Elm 68,Reach-1,6
Up Type=0
Dn Type=3
Dn Slope=0.005
Boundary for River Rch & Prof#=Elm 68,Reach-1,7
Up Type=0
Dn Type=3
Dn Slope=0.005

--- Elm 68.g01 (geometry) ---

Geom Title=Existing Conditions

River Reach=Elm 68,Reach-1
Reach XY= 30
      1526755.00      6766288.00      1526722.04      6766371.63
      1526545.32      6766448.76      1526205.00      6766788.00
      1526201.56      6766986.75      1526062.70      6767081.53
      1526051.44      6767236.53      1525958.55      6767339.47
      1525957.24      6767582.07      1526099.46      6767785.58
      1526110.52      6767890.43      1526241.79      6768024.37
      1526311.07      6768046.15      1526391.61      6768124.67
      1526408.53      6768236.72      1526448.62      6768279.99
      1526607.29      6768343.85      1526711.05      6768436.33
      1526808.40      6768395.84      1526934.93      6768488.65
      1527062.02      6768447.02      1527145.00      6768577.36
      1527307.30      6768643.83      1527448.83      6768780.14
      1527553.52      6768791.61      1527628.99      6768861.12
      1527647.65      6768944.33      1527512.70      6769034.33
      1527555.61      6769158.05      1527505.00      6769288.00

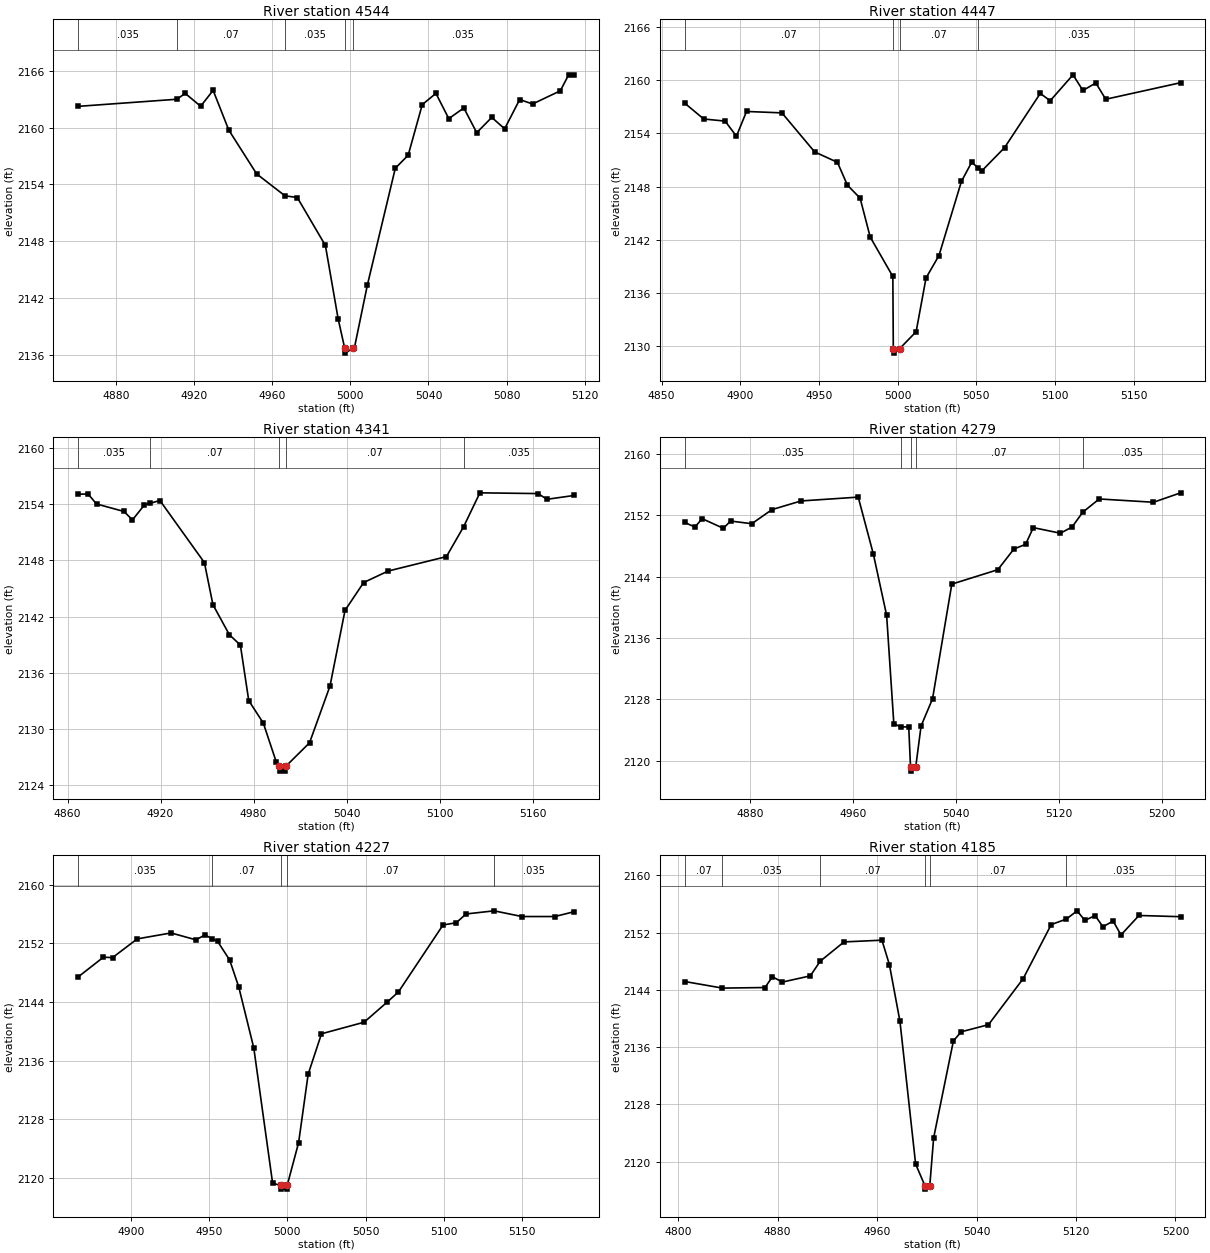
Type RM Length L Ch R = 1,4544,97,97,97
BEGIN DESCRIPTION:
Elm 68 4541
END DESCRIPTION:
XS GIS Cut Line= 3
      1526648.95      6766246.20      1526736.92      6766354.34
      1526824.30      6766428.48
#Sta/Elev= 30
  4860.6 2162.24  4911.1 2162.99  4915.4 2163.61  4923.3 2162.25  4929.7 2163.93
  4937.7 2159.74  4952.0 2155.10  4966.5 2152.79  4972.8 2152.61  4987.2 2147.54
  4993.7 2139.82  4997.1 2136.67  4997.4 2136.17  5001.1 2136.67  5002.0 2136.67
  5008.7 2143.37  5023.0 2155.70  5029.6 2157.08  5036.8 2162.42  5043.8 2163.61
  5050.4 2160.94  5058.1 2162.07  5064.7 2159.46  5072.4 2161.07  5079.0 2159.87
  5086.7 2162.96  5093.3 2162.49  5107.5 2163.88  5111.8 2165.57  5114.6 2165.57
#Mann=5,-1,0
  4860.6   0.035       0  4911.1    0.07       0  4966.5   0.035       0
  4997.1   0.035       0  5001.1   0.035       0
Bank Sta=4997.1,5001.1
Exp/Cntr=0.3,0.1

Type RM Length L Ch R = 1,4447,106,106,106
BEGIN DESCRIPTION:
Elm 68 4542
END DESCRIPTION:
XS GIS Cut Line= 3
      1526569.07      6766287.83      1526652.82      6766394.09
      1526795.30      6766503.92
#Sta/Elev= 30
  4864.7 2157.43  4876.8 2155.64  4890.4 2155.40  4897.6 2153.69  4904.0 2156.49
  4926.5 2156.33  4947.3 2151.92  4961.8 2150.74  4968.1 2148.17  4976.2 2146.69
  4982.6 2142.30  4997.0 2137.84  4997.3 2129.68  4997.6 2129.18  5001.3 2129.68
  5011.8 2131.60  5018.1 2137.68  5026.3 2140.20  5040.6 2148.59  5047.1 2150.75
  5051.0 2150.15  5053.5 2149.77  5068.0 2152.40  5090.7 2158.53  5097.0 2157.70
  5111.5 2160.63  5117.8 2158.86  5126.0 2159.71  5132.3 2157.87  5179.9 2159.74
#Mann=4,-1,0
  4864.7    0.07       0  4997.3    0.07       0  5001.3    0.07       0
  5051.0   0.035       0
Bank Sta=4997.3,5001.3
Exp/Cntr=0.3,0.1

Type RM Length L Ch R = 1,4341,62,62,62
BEGIN DESCRIPTION:
Elm 68 4543
END DESCRIPTION:
XS GIS Cut Line= 3
      1526506.56      6766319.06      1526561.04      6766440.50
      1526723.55      6766532.60
#Sta/Elev= 30
  4866.9 2155.07  4873.3 2155.08  4878.7 2154.02  4896.4 2153.22  4901.9 2152.32
  4909.6 2153.92  4913.2 2154.09  4919.6 2154.39  4948.3 2147.76  4953.8 2143.27
  4964.4 2140.06  4971.5 2138.96  4976.9 2133.03  4986.3 2130.63  4994.6 2126.50
  4996.7 2126.00  4997.0 2125.50  5000.5 2125.50  5000.7 2126.00  5016.1 2128.52
  5029.3 2134.58  5039.0 2142.66  5051.0 2145.63  5066.8 2146.86  5104.4 2148.40
  5115.5 2151.59  5126.0 2155.21  5163.5 2155.13  5169.3 2154.52  5186.8 2154.93
#Mann=5,-1,0
  4866.9   0.035       0  4913.2    0.07       0  4996.7    0.07       0
  5000.7    0.07       0  5115.5   0.035       0
Bank Sta=4996.7,5000.7
Exp/Cntr=0.3,0.1

Type RM Length L Ch R = 1,4279,52,52,52
BEGIN DESCRIPTION:
Elm 68 4544
END DESCRIPTION:
XS GIS Cut Line= 3
      1526435.37      6766327.74      1526514.36      6766479.63
      1526694.09      6766596.87
#Sta/Elev= 30
  4828.8 2151.06  4836.8 2150.47  4842.4 2151.56  4858.9 2150.30  4864.5 2151.25
  4881.0 2150.90  4896.7 2152.74  4919.3 2153.87  4963.8 2154.37  4975.6 2146.92
  4985.9 2138.95  4991.5 2124.83  4996.7 2124.39  5003.1 2124.39  5004.5 2119.12
  5004.7 2118.62  5008.5 2119.12  5012.7 2124.51  5021.6 2128.05  5036.6 2143.02
  5072.4 2144.90  5084.9 2147.60  5094.0 2148.21  5100.0 2150.39  5121.1 2149.66
  5130.2 2150.48  5138.5 2152.41  5151.3 2154.13  5193.5 2153.70  5214.6 2154.93
#Mann=5,-1,0
  4828.8   0.035       0  4996.7    0.07       0  5004.5    0.07       0
  5008.5    0.07       0  5138.5   0.035       0
Bank Sta=5004.5,5008.5
Exp/Cntr=0.3,0.1

Type RM Length L Ch R = 1,4227,42,42,42
BEGIN DESCRIPTION:
Elm 68 4226.984
END DESCRIPTION:
XS GIS Cut Line= 3
      1526411.07      6766400.67      1526477.25      6766516.61
      1526626.35      6766622.89
#Sta/Elev= 30
  4866.5 2147.44  4882.6 2150.13  4888.4 2150.07  4904.2 2152.63  4925.8 2153.44
  4941.6 2152.50  4947.4 2153.16  4952.2 2152.64  4955.5 2152.28  4963.2 2149.74
  4969.0 2146.05  4978.6 2137.72  4990.6 2119.27  4995.9 2118.96  4996.2 2118.46
  4999.7 2118.46  4999.9 2118.96  5007.2 2124.81  5013.3 2134.16  5021.8 2139.67
  5049.0 2141.25  5063.7 2143.99  5070.9 2145.38  5099.4 2154.53  5107.8 2154.83
  5114.1 2156.03  5132.0 2156.46  5149.8 2155.68  5170.7 2155.68  5183.1 2156.34
#Mann=5,-1,0
  4866.5   0.035       0  4952.2    0.07       0  4995.9    0.07       0
  4999.9    0.07       0  5132.0   0.035       0
Bank Sta=4995.9,4999.9
Exp/Cntr=0.3,0.1

Type RM Length L Ch R = 1,4185,64,64,64
BEGIN DESCRIPTION:
Elm 68 4185.03
END DESCRIPTION:
XS GIS Cut Line= 3
      1526343.39      6766381.61      1526451.01      6766551.71
      1526607.07      6766673.10
#Sta/Elev= 30
  4805.2 2145.17  4835.6 2144.25  4869.8 2144.33  4875.8 2145.83  4883.8 2145.09
  4906.3 2145.96  4914.2 2148.00  4933.4 2150.70  4963.9 2150.94  4969.9 2147.53
  4978.4 2139.60  4991.0 2119.69  4998.4 2116.68  4998.6 2116.18  5002.4 2116.68
  5005.5 2123.34  5021.4 2136.88  5027.7 2138.15  5049.6 2139.14  5077.5 2145.56
  5100.1 2153.12  5112.3 2153.89  5120.9 2155.04  5127.2 2153.70  5135.4 2154.38
  5141.7 2152.81  5149.9 2153.62  5156.2 2151.67  5170.7 2154.39  5204.2 2154.22
#Mann=6,-1,0
  4805.2    0.07       0  4835.6   0.035       0  4914.2    0.07       0
  4998.4    0.07       0  5002.4    0.07       0  5112.3   0.035       0
Bank Sta=4998.4,5002.4
Exp/Cntr=0.3,0.1

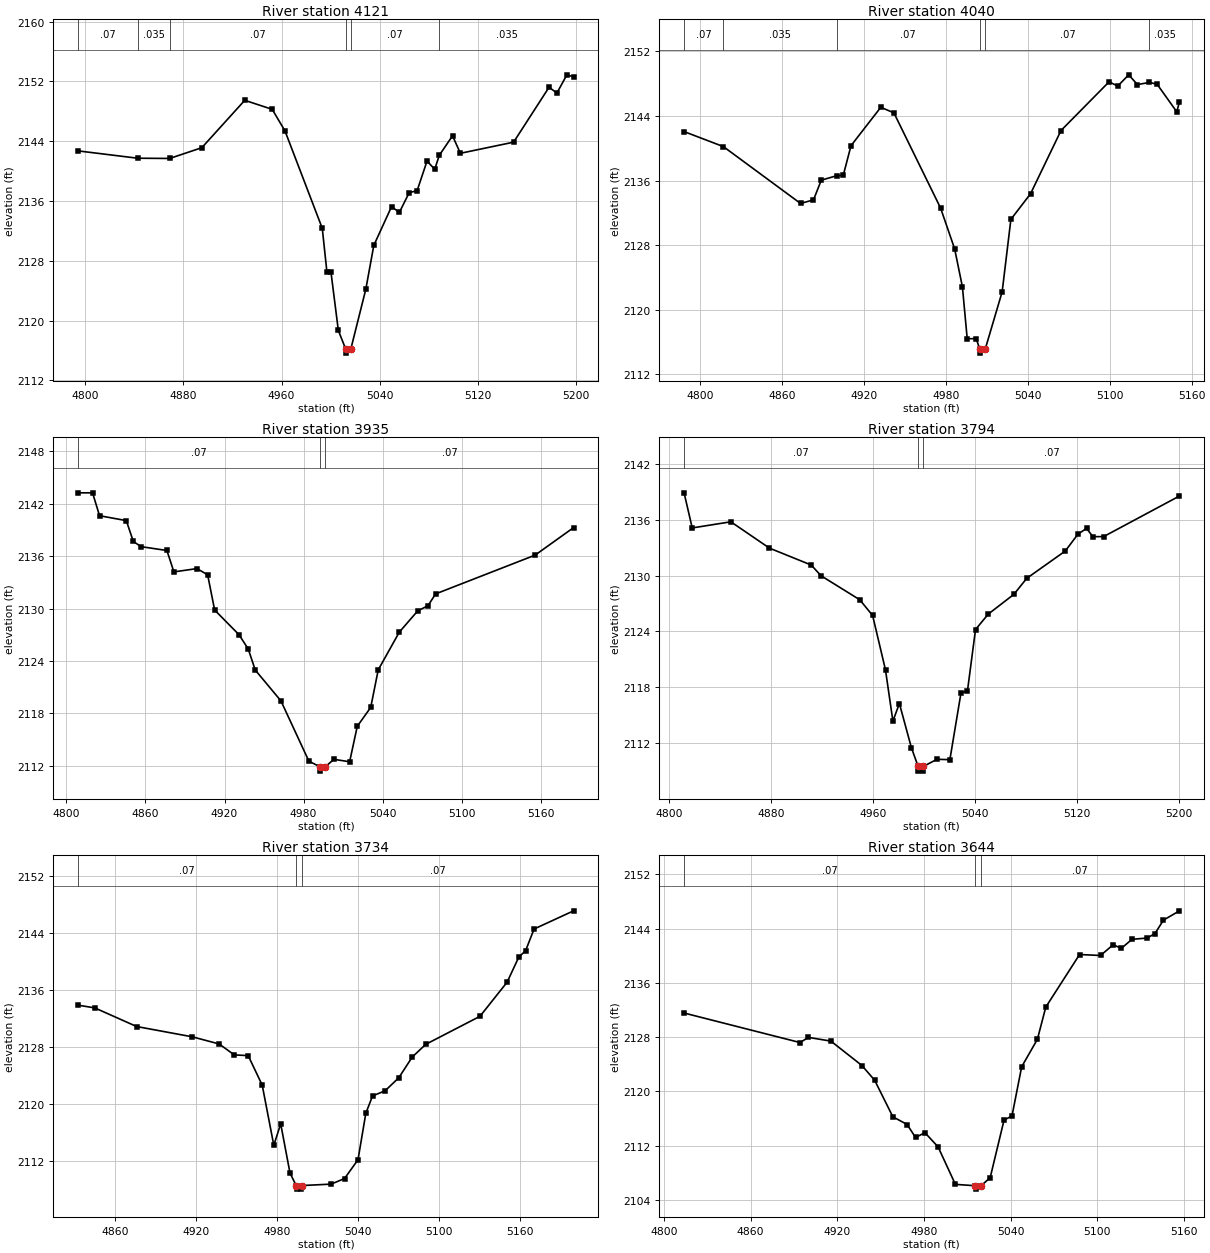
Type RM Length L Ch R = 1,4121,81,81,81
BEGIN DESCRIPTION:
Elm 68 4121.26
END DESCRIPTION:
XS GIS Cut Line= 3
      1526317.32      6766404.13      1526400.66      6766589.91
      1526558.56      6766713.11
#Sta/Elev= 30
  4794.2 2142.71  4842.7 2141.73  4868.8 2141.70  4895.0 2143.14  4930.0 2149.48
  4952.4 2148.27  4962.8 2145.38  4993.2 2132.35  4997.0 2126.48  5000.3 2126.48
  5006.3 2118.68  5012.4 2116.15  5012.6 2115.65  5016.4 2116.15  5028.7 2124.20
  5035.2 2130.06  5049.7 2135.26  5056.0 2134.47  5064.1 2137.13  5070.5 2137.38
  5078.6 2141.35  5084.9 2140.25  5088.6 2142.12  5099.4 2144.73  5105.8 2142.39
  5149.2 2143.88  5178.1 2151.23  5184.5 2150.45  5192.6 2152.89  5198.1 2152.62
#Mann=6,-1,0
  4794.2    0.07       0  4842.7   0.035       0  4868.8    0.07       0
  5012.4    0.07       0  5016.4    0.07       0  5088.6   0.035       0
Bank Sta=5012.4,5016.4
Exp/Cntr=0.3,0.1

Type RM Length L Ch R = 1,4040,105,105,105
BEGIN DESCRIPTION:
Elm 68 4040.18
END DESCRIPTION:
XS GIS Cut Line= 3
      1526242.68      6766463.19      1526343.37      6766647.20
      1526462.28      6766743.71
#Sta/Elev= 30
  4788.2 2142.07  4817.0 2140.21  4873.5 2133.17  4883.0 2133.61  4888.7 2136.05
  4899.9 2136.60  4904.8 2136.65  4910.5 2140.33  4932.3 2145.08  4941.9 2144.39
  4976.1 2132.60  4986.4 2127.54  4992.1 2122.83  4995.6 2116.42  5002.2 2116.42
  5004.8 2115.13  5005.1 2114.63  5008.8 2115.13  5021.2 2122.22  5027.6 2131.20
  5042.0 2134.37  5064.3 2142.20  5099.5 2148.23  5105.9 2147.71  5113.9 2149.10
  5120.3 2147.89  5129.1 2148.16  5134.7 2147.94  5149.1 2144.52  5151.1 2145.75
#Mann=6,-1,0
  4788.2    0.07       0  4817.0   0.035       0  4899.9    0.07       0
  5004.8    0.07       0  5008.8    0.07       0  5129.1   0.035       0
Bank Sta=5004.8,5008.8
Exp/Cntr=0.3,0.1

Type RM Length L Ch R = 1,3935,141,141,141
BEGIN DESCRIPTION:
Elm 68 3934.56
END DESCRIPTION:
XS GIS Cut Line= 3
      1526206.23      6766543.07      1526272.19      6766728.80
      1526428.41      6766815.59
#Sta/Elev= 30
  4809.0 2143.25  4819.9 2143.25  4825.2 2140.63  4845.5 2140.07  4850.8 2137.69
  4856.7 2137.09  4876.3 2136.65  4881.6 2134.20  4899.1 2134.58  4907.2 2133.87
  4912.5 2129.84  4931.0 2127.01  4938.0 2125.37  4943.3 2122.97  4962.8 2119.44
  4984.0 2112.54  4992.4 2111.90  4992.7 2111.40  4996.4 2111.90  5003.0 2112.75
  5014.9 2112.47  5020.7 2116.53  5030.9 2118.69  5036.6 2122.99  5052.6 2127.31
  5066.5 2129.73  5074.4 2130.34  5080.1 2131.68  5155.6 2136.12  5184.8 2139.27
#Mann=3,-1,0
  4809.0    0.07       0  4992.4    0.07       0  4996.4    0.07       0
Bank Sta=4992.4,4996.4
Exp/Cntr=0.3,0.1

Type RM Length L Ch R = 1,3794,60,60,60
BEGIN DESCRIPTION:
Elm 68 3794.2
END DESCRIPTION:
XS GIS Cut Line= 3
      1526018.70      6766808.66      1526204.48      6766836.44
      1526404.15      6766815.60
#Sta/Elev= 30
  4811.5 2138.88  4817.9 2135.11  4848.2 2135.77  4878.5 2132.94  4911.2 2131.13
  4919.0 2129.97  4949.3 2127.40  4959.4 2125.71  4969.5 2119.86  4975.3 2114.37
  4980.4 2116.26  4989.8 2111.52  4995.1 2109.50  4995.3 2109.00  4998.8 2109.00
  4999.1 2109.50  5009.9 2110.27  5020.0 2110.23  5028.7 2117.39  5033.8 2117.62
  5040.1 2124.20  5050.1 2125.86  5070.2 2127.98  5080.3 2129.70  5110.5 2132.63
  5120.5 2134.45  5127.2 2135.06  5132.2 2134.17  5140.6 2134.18  5200.1 2138.54
#Mann=3,-1,0
  4811.5    0.07       0  4995.1    0.07       0  4999.1    0.07       0
Bank Sta=4995.1,4999.1
Exp/Cntr=0.3,0.1

Type RM Length L Ch R = 1,3734,90,90,90
BEGIN DESCRIPTION:
Elm 68 3733.59
END DESCRIPTION:
XS GIS Cut Line= 3
      1526043.06      6766855.54      1526202.74      6766897.20
      1526404.17      6766879.84
#Sta/Elev= 30
  4832.4 2133.85  4844.7 2133.47  4875.7 2130.86  4917.1 2129.41  4936.9 2128.41
  4948.1 2126.88  4958.4 2126.78  4968.8 2122.64  4977.4 2114.20  4982.5 2117.22
  4989.4 2110.31  4994.0 2108.56  4994.3 2108.06  4997.8 2108.06  4998.0 2108.56
  5019.8 2108.76  5029.8 2109.54  5039.8 2112.18  5045.6 2118.70  5050.6 2121.13
  5059.9 2121.85  5070.0 2123.67  5080.0 2126.58  5090.0 2128.36  5130.2 2132.29
  5150.3 2137.07  5159.0 2140.60  5164.0 2141.48  5170.3 2144.53  5199.6 2147.08
#Mann=3,-1,0
  4832.4    0.07       0  4994.0    0.07       0  4998.0    0.07       0
Bank Sta=4994,4998
Exp/Cntr=0.3,0.1

Type RM Length L Ch R = 1,3644,99,99,99
BEGIN DESCRIPTION:
Elm 68 3643.81
END DESCRIPTION:
XS GIS Cut Line= 3
      1526041.28      6766891.99      1526206.22      6766989.21
      1526345.14      6767049.99
#Sta/Elev= 30
  4813.9 2131.55  4894.2 2127.20  4900.0 2127.96  4915.6 2127.41  4937.1 2123.81
  4945.9 2121.64  4958.5 2116.26  4968.4 2115.12  4974.2 2113.21  4980.7 2113.92
  4989.8 2111.83  5001.8 2106.30  5015.6 2106.10  5015.9 2105.60  5019.6 2106.10
  5025.9 2107.29  5035.5 2115.78  5041.0 2116.38  5047.7 2123.63  5058.6 2127.68
  5064.4 2132.42  5087.8 2140.17  5102.3 2140.03  5111.2 2141.63  5116.6 2141.06
  5124.1 2142.41  5134.6 2142.60  5140.0 2143.26  5145.9 2145.24  5157.0 2146.61
#Mann=3,-1,0
  4813.9    0.07       0  5015.6    0.07       0  5019.6    0.07       0
Bank Sta=5015.6,5019.6
Exp/Cntr=0.3,0.1

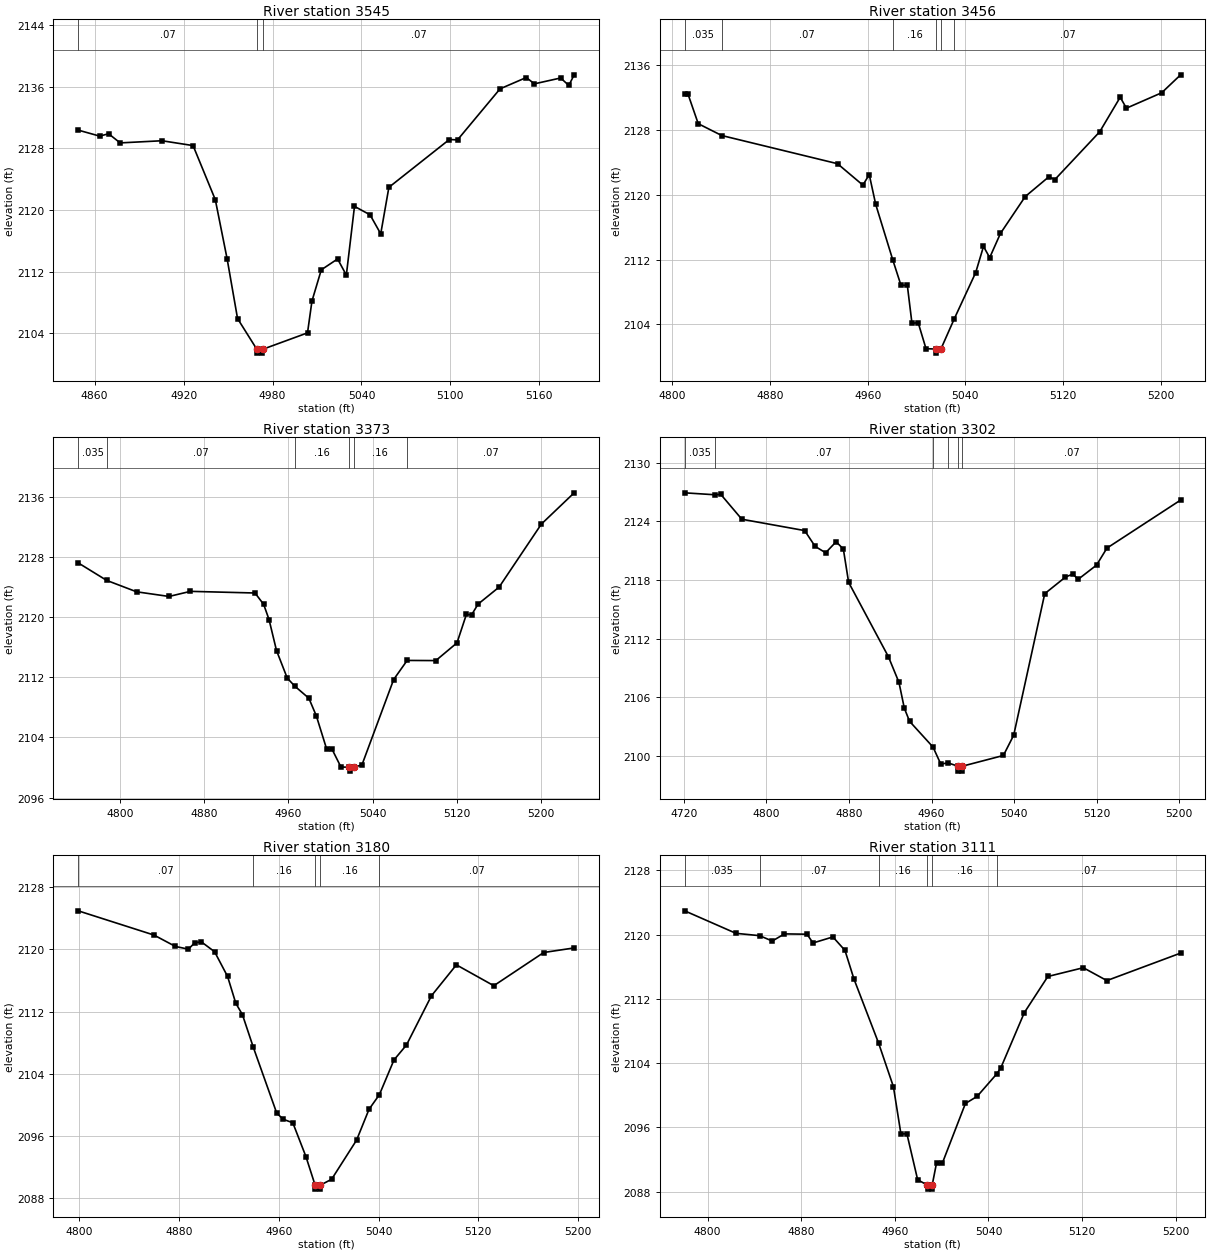
Type RM Length L Ch R = 1,3545,89,89,89
BEGIN DESCRIPTION:
Elm 68 3544.97
END DESCRIPTION:
XS GIS Cut Line= 3
      1526039.54      6766914.54      1526124.62      6767041.30
      1526290.66      6767115.67
#Sta/Elev= 30
  4848.9 2130.38  4863.4 2129.60  4869.4 2129.91  4877.2 2128.72  4905.4 2129.00
  4926.4 2128.37  4941.4 2121.34  4949.4 2113.63  4956.4 2105.91  4969.4 2101.92
  4969.7 2101.42  4973.2 2101.42  4973.4 2101.92  5003.6 2104.05  5006.6 2108.18
  5012.9 2112.24  5023.9 2113.65  5029.8 2111.55  5035.3 2120.48  5045.8 2119.38
  5053.0 2116.91  5058.5 2122.95  5099.3 2129.16  5104.8 2129.11  5133.5 2135.74
  5151.2 2137.21  5156.7 2136.39  5174.4 2137.15  5179.9 2136.18  5183.5 2137.56
#Mann=3,-1,0
  4848.9    0.07       0  4969.4    0.07       0  4973.4    0.07       0
Bank Sta=4969.4,4973.4
Exp/Cntr=0.3,0.1

Type RM Length L Ch R = 1,3456,83,83,83
BEGIN DESCRIPTION:
Elm 68 3455.65
END DESCRIPTION:
XS GIS Cut Line= 3
      1525874.62      6767041.30      1526049.97      6767091.64
      1526270.26      6767131.54
#Sta/Elev= 30
  4810.1 2132.35  4812.9 2132.35  4821.2 2128.74  4840.5 2127.28  4935.3 2123.81
  4956.1 2121.17  4961.3 2122.47  4966.6 2118.80  4980.6 2111.95  4987.3 2108.83
  4992.5 2108.83  4996.3 2104.15  5001.4 2104.22  5007.8 2101.02  5016.0 2100.97
  5016.2 2100.47  5020.0 2100.97  5031.0 2104.71  5048.5 2110.39  5054.9 2113.61
  5060.0 2112.24  5068.8 2115.22  5089.1 2119.76  5108.4 2122.19  5113.4 2121.86
  5150.1 2127.74  5166.9 2132.00  5172.0 2130.65  5200.9 2132.55  5216.4 2134.76
#Mann=6,-1,0
  4810.1   0.035       0  4840.5    0.07       0  4980.6    0.16       0
  5016.0    0.07       0  5020.0    0.16       0  5031.0    0.07       0
Bank Sta=5016,5020
Exp/Cntr=0.3,0.1

Type RM Length L Ch R = 1,3373,71,71,71
BEGIN DESCRIPTION:
Elm 68 3373.32
END DESCRIPTION:
XS GIS Cut Line= 3
      1525820.77      6767126.36      1526053.44      6767174.98
      1526286.04      6767188.86
#Sta/Elev= 30
  4760.6 2127.25  4787.6 2124.92  4816.0 2123.40  4846.8 2122.78  4867.1 2123.46
  4928.4 2123.24  4936.6 2121.73  4941.7 2119.71  4948.8 2115.58  4959.0 2111.91
  4966.1 2110.84  4979.5 2109.23  4986.6 2106.88  4996.5 2102.41  5001.6 2102.41
  5009.9 2100.08  5017.9 2100.02  5018.1 2099.52  5021.9 2100.02  5029.9 2100.35
  5060.0 2111.72  5072.8 2114.26  5100.0 2114.24  5120.1 2116.60  5129.0 2120.38
  5134.0 2120.34  5140.1 2121.76  5160.1 2124.03  5200.2 2132.42  5231.3 2136.58
#Mann=6,-1,0
  4760.6   0.035       0  4787.6    0.07       0  4966.1    0.16       0
  5017.9    0.07       0  5021.9    0.16       0  5072.8    0.07       0
Bank Sta=5017.9,5021.9
Exp/Cntr=0.3,0.1

Type RM Length L Ch R = 1,3302,122,122,122
BEGIN DESCRIPTION:
Elm 68 3301.64
END DESCRIPTION:
XS GIS Cut Line= 3
      1525770.49      6767195.82      1526044.76      6767244.42
      1526246.17      6767261.79
#Sta/Elev= 30
  4720.7 2126.91  4750.2 2126.71  4755.7 2126.75  4776.1 2124.21  4837.0 2123.05
  4847.1 2121.44  4857.3 2120.78  4867.5 2121.91  4874.5 2121.16  4879.6 2117.76
  4918.2 2110.15  4928.4 2107.53  4933.6 2104.89  4938.7 2103.55  4961.4 2100.92
  4969.0 2099.17  4975.7 2099.31  4985.7 2098.96  4985.9 2098.46  4989.4 2098.46
  4989.7 2098.96  5029.6 2100.06  5039.6 2102.13  5069.7 2116.60  5089.8 2118.30
  5097.0 2118.61  5102.0 2118.06  5119.9 2119.52  5130.0 2121.26  5201.4 2126.17
#Mann=6,-1,0
  4720.7   0.035       0  4750.2    0.07       0  4961.4    0.16       0
  4975.7    0.07       0  4985.7    0.07       0  4989.7    0.07       0
Bank Sta=4985.7,4989.7
Exp/Cntr=0.3,0.1

Type RM Length L Ch R = 1,3180,69,69,69
BEGIN DESCRIPTION:
Elm 68 3180.23
END DESCRIPTION:
XS GIS Cut Line= 3
      1525770.49      6767275.69      1525957.95      6767332.96
      1526159.37      6767327.76
#Sta/Elev= 30
  4799.3 2124.98  4860.0 2121.86  4877.2 2120.39  4887.6 2120.04  4892.8 2120.88
  4898.1 2120.97  4908.6 2119.71  4919.0 2116.53  4925.6 2113.07  4930.9 2111.61
  4939.7 2107.37  4958.4 2098.92  4963.6 2098.12  4971.3 2097.67  4981.8 2093.32
  4989.2 2089.62  4989.4 2089.12  4992.9 2089.12  4993.2 2089.62  5002.4 2090.39
  5022.4 2095.43  5032.4 2099.41  5040.7 2101.29  5052.4 2105.77  5062.4 2107.69
  5082.4 2114.03  5102.4 2118.02  5132.4 2115.33  5172.4 2119.61  5196.8 2120.20
#Mann=5,-1,0
  4799.3    0.07       0  4939.7    0.16       0  4989.2    0.07       0
  4993.2    0.16       0  5040.7    0.07       0
Bank Sta=4989.2,4993.2
Exp/Cntr=0.3,0.1

Type RM Length L Ch R = 1,3111,71,71,71
BEGIN DESCRIPTION:
Elm 68 3111.35
END DESCRIPTION:
XS GIS Cut Line= 3
      1525742.68      6767345.12      1525951.01      6767400.67
      1526157.58      6767376.37
#Sta/Elev= 30
  4780.5 2122.95  4824.3 2120.15  4844.5 2119.86  4855.3 2119.19  4865.7 2120.08
  4885.0 2120.04  4890.1 2118.95  4907.1 2119.70  4917.4 2118.03  4925.1 2114.46
  4946.2 2106.46  4958.8 2101.06  4965.2 2095.19  4970.3 2095.21  4979.5 2089.48
  4987.9 2088.82  4988.1 2088.32  4991.6 2088.32  4991.9 2088.82  4995.6 2091.56
  5000.6 2091.56  5020.3 2098.98  5030.3 2099.86  5047.0 2102.65  5050.5 2103.40
  5070.6 2110.28  5090.7 2114.78  5121.0 2115.87  5141.1 2114.27  5204.1 2117.69
#Mann=6,-1,0
  4780.5   0.035       0  4844.5    0.07       0  4946.2    0.16       0
  4987.9    0.07       0  4991.9    0.16       0  5047.0    0.07       0
Bank Sta=4987.9,4991.9
Exp/Cntr=0.3,0.1

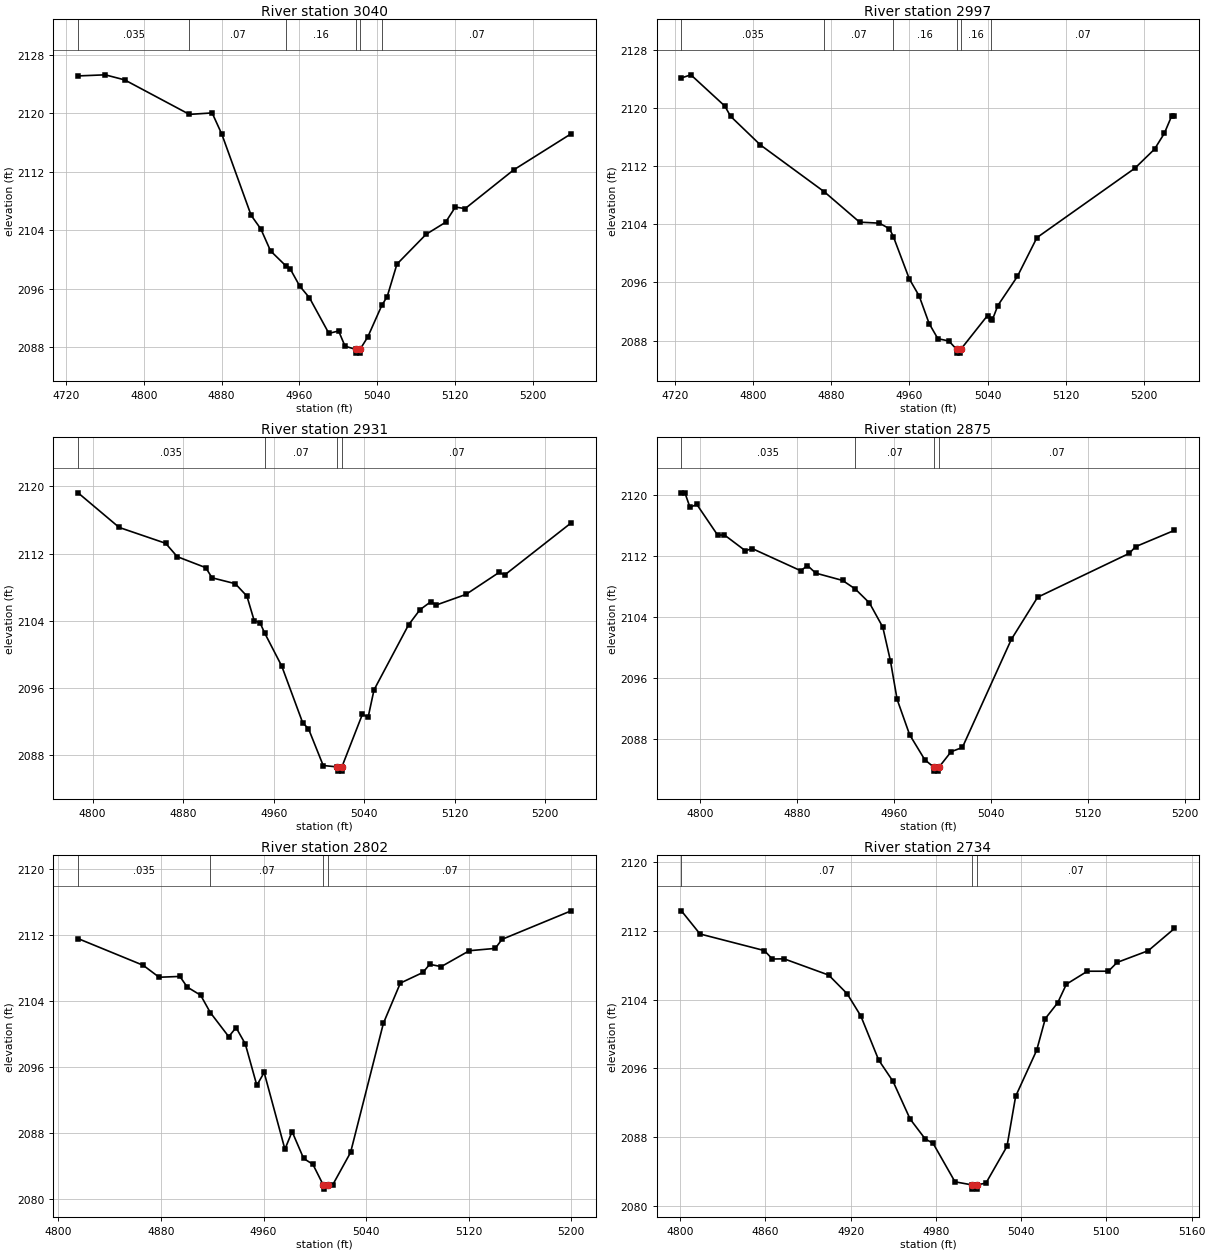
Type RM Length L Ch R = 1,3040,43,43,43
BEGIN DESCRIPTION:
Elm 68 3039.88
END DESCRIPTION:
XS GIS Cut Line= 3
      1525687.08      6767466.64      1525963.16      6767471.85
      1526194.07      6767463.17
#Sta/Elev= 30
  4732.3 2125.11  4760.2 2125.26  4780.2 2124.57  4846.8 2119.85  4870.2 2120.05
  4880.2 2117.13  4910.3 2106.05  4920.3 2104.18  4930.3 2101.18  4945.7 2099.18
  4950.3 2098.77  4960.3 2096.37  4970.3 2094.77  4990.3 2089.90  5000.3 2090.23
  5006.9 2088.15  5018.3 2087.70  5018.5 2087.20  5022.0 2087.20  5022.3 2087.70
  5030.3 2089.41  5044.7 2093.72  5050.3 2094.94  5060.3 2099.37  5090.3 2103.45
  5110.3 2105.09  5120.4 2107.18  5130.4 2106.96  5180.4 2112.26  5239.5 2117.20
#Mann=6,-1,0
  4732.3   0.035       0  4846.8    0.07       0  4945.7    0.16       0
  5018.3    0.07       0  5022.3    0.16       0  5044.7    0.07       0
Bank Sta=5018.3,5022.3
Exp/Cntr=0.3,0.1

Type RM Length L Ch R = 1,2997,66,66,66
BEGIN DESCRIPTION:
Elm 68 2996.63
END DESCRIPTION:
XS GIS Cut Line= 3
      1525685.41      6767560.39      1525947.53      6767515.26
      1526185.42      6767504.84
#Sta/Elev= 30
  4726.9 2124.17  4736.6 2124.60  4771.3 2120.30  4777.2 2118.89  4807.7 2114.94
  4873.1 2108.48  4909.1 2104.31  4929.4 2104.17  4939.6 2103.40  4943.6 2102.32
  4959.9 2096.50  4970.0 2094.14  4980.2 2090.34  4989.1 2088.26  5000.4 2087.94
  5008.4 2086.77  5008.6 2086.27  5012.1 2086.27  5012.4 2086.77  5039.9 2091.45
  5043.6 2091.03  5044.9 2090.88  5050.4 2092.82  5070.4 2096.83  5090.4 2102.18
  5190.5 2111.73  5210.6 2114.36  5220.6 2116.53  5228.3 2118.98  5231.0 2118.98
#Mann=6,-1,0
  4726.9   0.035       0  4873.1    0.07       0  4943.6    0.16       0
  5008.4    0.07       0  5012.4    0.16       0  5043.6    0.07       0
Bank Sta=5008.4,5012.4
Exp/Cntr=0.3,0.1

Type RM Length L Ch R = 1,2931,56,56,56
BEGIN DESCRIPTION:
Elm 68 2930.97
END DESCRIPTION:
XS GIS Cut Line= 3
      1525749.58      6767628.11      1525961.42      6767579.49
      1526176.71      6767543.03
#Sta/Elev= 30
  4787.1 2119.23  4823.4 2115.11  4864.5 2113.22  4874.7 2111.63  4899.9 2110.32
  4905.5 2109.11  4926.0 2108.41  4936.3 2106.93  4942.7 2104.02  4947.9 2103.75
  4952.0 2102.53  4967.1 2098.59  4985.6 2091.84  4990.7 2091.14  5003.7 2086.76
  5016.2 2086.59  5016.5 2086.09  5020.0 2086.09  5020.2 2086.59  5038.4 2092.88
  5043.4 2092.50  5048.6 2095.76  5079.1 2103.50  5089.2 2105.31  5098.7 2106.25
  5103.8 2105.88  5129.8 2107.13  5159.1 2109.75  5164.2 2109.46  5222.8 2115.65
#Mann=4,-1,0
  4787.1   0.035       0  4952.0    0.07       0  5016.2    0.07       0
  5020.2    0.07       0
Bank Sta=5016.2,5020.2
Exp/Cntr=0.3,0.1

Type RM Length L Ch R = 1,2875,73,73,73
BEGIN DESCRIPTION:
Elm 68 2875.32
END DESCRIPTION:
XS GIS Cut Line= 3
      1525794.79      6767716.63      1525997.88      6767621.16
      1526178.46      6767598.59
#Sta/Elev= 30
  4784.8 2120.29  4787.7 2120.29  4791.9 2118.38  4797.5 2118.77  4814.7 2114.73
  4820.3 2114.75  4837.6 2112.67  4843.1 2112.97  4883.2 2110.05  4888.7 2110.74
  4895.5 2109.74  4917.6 2108.78  4928.0 2107.67  4939.8 2105.82  4950.8 2102.64
  4957.1 2098.21  4962.6 2093.15  4972.9 2088.51  4985.4 2085.22  4993.0 2084.22
  4993.2 2083.72  4996.7 2083.72  4997.0 2084.22  5007.1 2086.27  5016.4 2086.83
  5056.7 2101.02  5078.4 2106.57  5154.0 2112.34  5159.1 2113.21  5191.2 2115.36
#Mann=4,-1,0
  4784.8   0.035       0  4928.0    0.07       0  4993.0    0.07       0
  4997.0    0.07       0
Bank Sta=4993,4997
Exp/Cntr=0.3,0.1

Type RM Length L Ch R = 1,2802,68,68,68
BEGIN DESCRIPTION:
Elm 68 2801.9
END DESCRIPTION:
XS GIS Cut Line= 3
      1525850.32      6767780.88      1526020.45      6767688.87
      1526200.48      6767624.82
#Sta/Elev= 30
  4815.4 2111.54  4866.2 2108.30  4878.6 2106.85  4894.8 2106.95  4900.5 2105.66
  4911.0 2104.67  4918.5 2102.57  4932.9 2099.64  4938.6 2100.74  4945.8 2098.76
  4954.8 2093.73  4960.5 2095.30  4976.7 2085.98  4982.3 2088.12  4991.3 2084.86
  4998.5 2084.15  5006.6 2081.64  5006.8 2081.14  5010.6 2081.64  5013.9 2081.64
  5027.9 2085.59  5053.5 2101.27  5066.7 2106.14  5084.3 2107.43  5089.6 2108.42
  5098.6 2108.14  5120.5 2110.07  5140.7 2110.35  5146.0 2111.45  5199.9 2114.91
#Mann=4,-1,0
  4815.4   0.035       0  4918.5    0.07       0  5006.6    0.07       0
  5010.6    0.07       0
Bank Sta=5006.6,5010.6
Exp/Cntr=0.3,0.1

Type RM Length L Ch R = 1,2734,98,98,98
BEGIN DESCRIPTION:
Elm 68 2733.76
END DESCRIPTION:
XS GIS Cut Line= 3
      1525879.84      6767829.49      1526056.91      6767744.42
      1526180.08      6767657.68
#Sta/Elev= 30
  4800.8 2114.31  4813.9 2111.62  4859.2 2109.69  4864.8 2108.71  4873.1 2108.73
  4904.5 2106.84  4917.5 2104.67  4927.1 2102.09  4939.7 2096.96  4949.8 2094.48
  4961.8 2090.11  4972.4 2087.80  4978.0 2087.28  4993.4 2082.81  5005.1 2082.46
  5005.4 2081.96  5008.9 2081.96  5009.1 2082.46  5015.2 2082.66  5030.0 2086.93
  5036.1 2092.75  5050.9 2098.10  5057.0 2101.79  5065.7 2103.62  5071.8 2105.78
  5086.6 2107.29  5101.4 2107.29  5107.5 2108.31  5129.5 2109.68  5147.9 2112.26
#Mann=3,-1,0
  4800.8    0.07       0  5005.1    0.07       0  5009.1    0.07       0
Bank Sta=5005.1,5009.1
Exp/Cntr=0.3,0.1

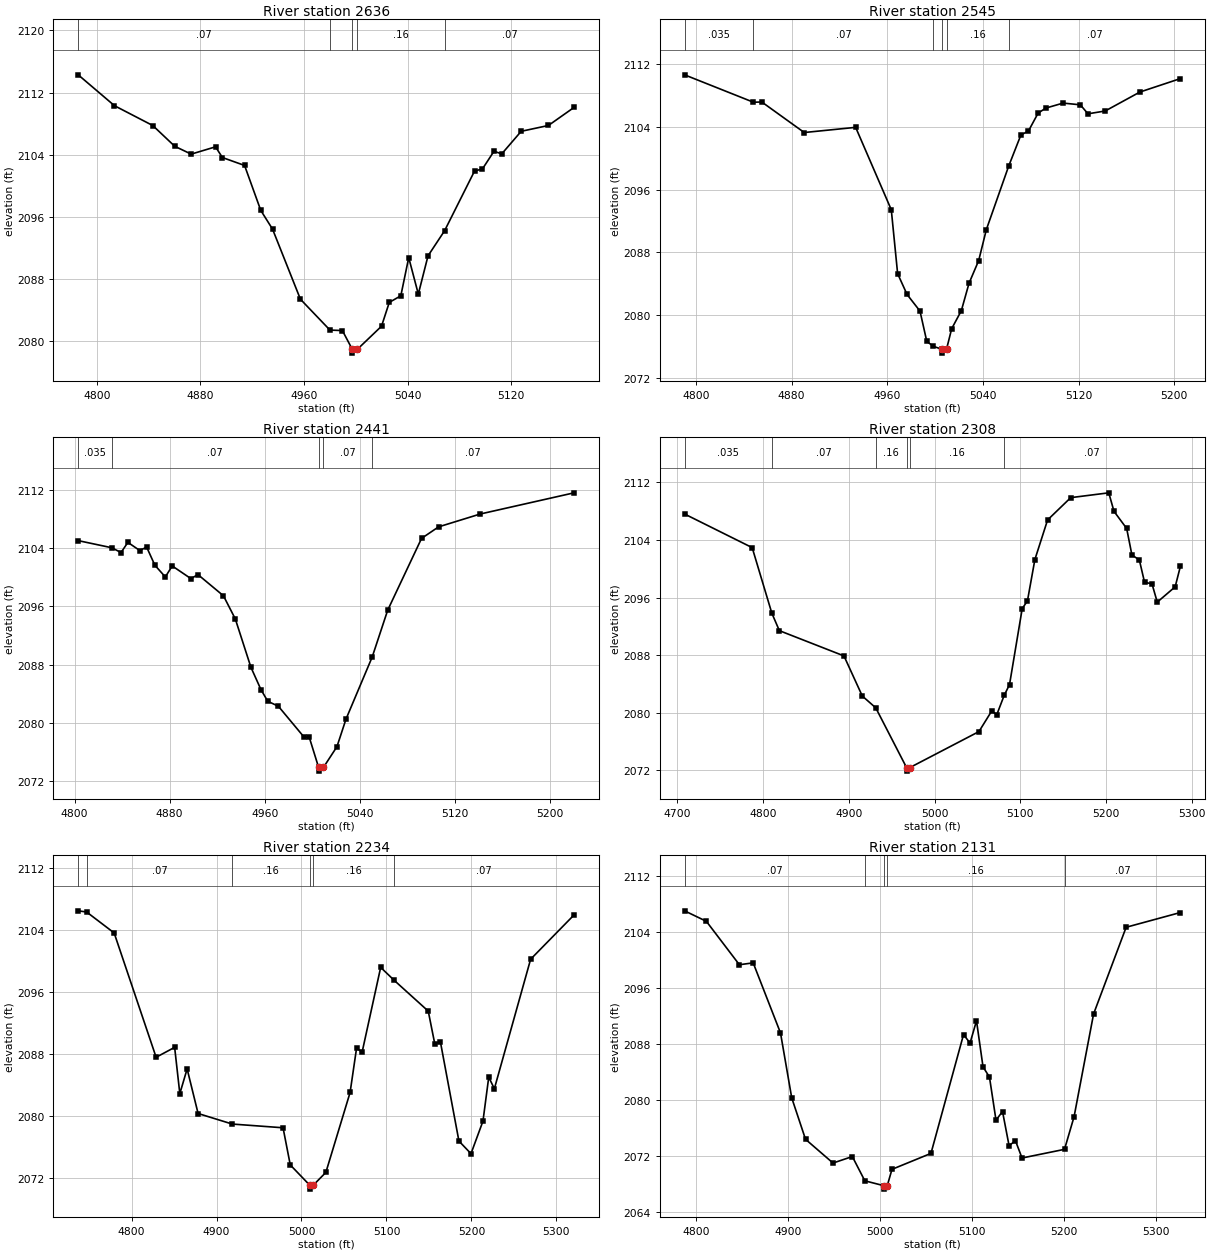
Type RM Length L Ch R = 1,2636,91,91,91
BEGIN DESCRIPTION:
Elm 68 2635.61
END DESCRIPTION:
XS GIS Cut Line= 3
      1525905.83      6767904.16      1526108.99      6767822.55
      1526244.44      6767730.51
#Sta/Elev= 30
  4785.7 2114.28  4813.7 2110.30  4843.3 2107.74  4860.2 2105.07  4872.9 2104.06
  4891.7 2105.00  4897.0 2103.62  4914.1 2102.60  4926.6 2096.81  4935.7 2094.39
  4957.2 2085.36  4980.0 2081.38  4989.6 2081.32  4997.2 2078.91  4997.4 2078.41
  5001.2 2078.91  5019.8 2081.88  5025.8 2084.95  5034.7 2085.80  5040.8 2090.72
  5048.2 2086.02  5055.7 2090.95  5068.5 2094.19  5091.6 2101.88  5097.7 2102.15
  5106.6 2104.43  5112.6 2104.09  5127.6 2107.00  5148.6 2107.75  5168.4 2110.08
#Mann=5,-1,0
  4785.7    0.07       0  4980.0    0.16       0  4997.2    0.07       0
  5001.2    0.16       0  5068.5    0.07       0
Bank Sta=4997.2,5001.2
Exp/Cntr=0.3,0.1

Type RM Length L Ch R = 1,2545,104,104,104
BEGIN DESCRIPTION:
Elm 68 2544.63
END DESCRIPTION:
XS GIS Cut Line= 3
      1525931.87      6767987.49      1526121.15      6767912.83
      1526287.60      6767782.79
#Sta/Elev= 30
  4790.5 2110.68  4848.1 2107.18  4855.1 2107.21  4890.6 2103.31  4933.6 2103.97
  4963.4 2093.44  4968.7 2085.28  4976.6 2082.62  4987.4 2080.50  4993.1 2076.62
  4998.6 2076.00  5005.6 2075.63  5005.8 2075.13  5009.6 2075.63  5013.9 2078.25
  5022.0 2080.56  5028.4 2084.05  5036.5 2086.96  5042.9 2090.91  5061.5 2098.99
  5071.8 2103.00  5078.1 2103.50  5086.2 2105.79  5092.6 2106.43  5107.1 2107.07
  5121.5 2106.85  5127.9 2105.70  5142.3 2106.06  5171.3 2108.48  5205.2 2110.20
#Mann=6,-1,0
  4790.5   0.035       0  4848.1    0.07       0  4998.6    0.16       0
  5005.6    0.07       0  5009.6    0.16       0  5061.5    0.07       0
Bank Sta=5005.6,5009.6
Exp/Cntr=0.3,0.1

Type RM Length L Ch R = 1,2441,133,133,133
BEGIN DESCRIPTION:
Elm 68 2440.82
END DESCRIPTION:
XS GIS Cut Line= 3
      1526029.16      6768081.21      1526197.53      6767984.01
      1526365.94      6767838.17
#Sta/Elev= 30
  4803.1 2105.03  4831.4 2104.05  4839.1 2103.39  4844.9 2104.79  4854.9 2103.67
  4860.7 2104.14  4867.6 2101.65  4876.4 2100.04  4882.2 2101.55  4898.0 2099.80
  4903.8 2100.37  4925.3 2097.45  4935.3 2094.26  4948.4 2087.63  4956.9 2084.54
  4962.6 2082.95  4971.5 2082.27  4993.2 2078.01  4997.5 2078.01  5005.4 2073.85
  5005.6 2073.35  5009.4 2073.85  5020.8 2076.71  5028.4 2080.49  5050.5 2089.05
  5063.5 2095.47  5092.0 2105.34  5106.3 2106.92  5141.4 2108.69  5220.3 2111.60
#Mann=5,-1,0
  4803.1   0.035       0  4831.4    0.07       0  5005.4    0.07       0
  5009.4    0.07       0  5050.5    0.07       0
Bank Sta=5005.4,5009.4
Exp/Cntr=0.3,0.1

Type RM Length L Ch R = 1,2308,74,74,74
BEGIN DESCRIPTION:
Elm 68 2308.03
END DESCRIPTION:
XS GIS Cut Line= 3
      1526041.25      6768154.16      1526305.17      6768053.45
      1526476.14      6767811.68
#Sta/Elev= 30
  4708.3 2107.60  4787.2 2102.93  4810.1 2093.84  4818.9 2091.40  4894.3 2087.89
  4915.7 2082.32  4931.4 2080.68  4967.3 2072.39  4967.5 2071.89  4971.3 2072.39
  5051.8 2077.38  5066.6 2080.22  5072.7 2079.75  5081.3 2082.42  5087.5 2083.91
  5102.3 2094.46  5108.4 2095.53  5117.1 2101.28  5131.9 2106.77  5158.9 2109.87
  5203.3 2110.54  5209.4 2107.97  5224.2 2105.59  5230.3 2101.92  5239.0 2101.21
  5245.1 2098.10  5253.7 2097.92  5259.9 2095.36  5280.8 2097.49  5286.9 2100.34
#Mann=6,-1,0
  4708.3   0.035       0  4810.1    0.07       0  4931.4    0.16       0
  4967.3    0.07       0  4971.3    0.16       0  5081.3    0.07       0
Bank Sta=4967.3,4971.3
Exp/Cntr=0.3,0.1

Type RM Length L Ch R = 1,2234,103,103,103
BEGIN DESCRIPTION:
Elm 68 2234.02
END DESCRIPTION:
XS GIS Cut Line= 3
      1526150.66      6768251.37      1526376.35      6768088.17
      1526605.52      6767886.78
#Sta/Elev= 30
  4737.2 2106.42  4747.1 2106.27  4779.5 2103.57  4828.9 2087.54  4850.7 2088.82
  4856.8 2082.85  4865.4 2086.04  4878.3 2080.29  4918.5 2078.93  4978.3 2078.45
  4986.8 2073.66  5009.8 2071.04  5010.0 2070.54  5013.8 2071.04  5028.7 2072.70
  5057.2 2083.00  5064.8 2088.70  5071.4 2088.22  5093.2 2099.13  5109.2 2097.45
  5149.2 2093.49  5156.8 2089.31  5163.5 2089.53  5185.3 2076.74  5199.5 2075.11
  5213.6 2079.31  5220.4 2084.98  5227.0 2083.48  5269.7 2100.18  5320.8 2105.89
#Mann=6,-1,0
  4737.2   0.035       0  4747.1    0.07       0  4918.5    0.16       0
  5009.8    0.07       0  5013.8    0.16       0  5109.2    0.07       0
Bank Sta=5009.8,5013.8
Exp/Cntr=0.3,0.1

Type RM Length L Ch R = 1,2131,90,90,90
BEGIN DESCRIPTION:
Elm 68 2130.57
END DESCRIPTION:
XS GIS Cut Line= 3
      1526228.75      6768305.21      1526407.60      6768183.66
      1526636.76      6767956.24
#Sta/Elev= 30
  4787.5 2107.06  4811.2 2105.56  4847.1 2099.35  4862.1 2099.62  4891.8 2089.60
  4904.0 2080.32  4919.0 2074.39  4948.9 2070.99  4969.9 2071.92  4983.5 2068.45
  5003.9 2067.76  5004.1 2067.26  5007.9 2067.76  5013.0 2070.09  5055.4 2072.37
  5090.8 2089.36  5097.9 2088.15  5104.9 2091.34  5112.0 2084.74  5119.0 2083.29
  5126.1 2077.13  5133.2 2078.36  5140.3 2073.49  5147.3 2074.17  5154.4 2071.71
  5200.6 2072.95  5211.0 2077.62  5232.2 2092.31  5267.6 2104.71  5326.6 2106.82
#Mann=5,-1,0
  4787.5    0.07       0  4983.5    0.16       0  5003.9    0.07       0
  5007.9    0.16       0  5200.6    0.07       0
Bank Sta=5003.9,5007.9
Exp/Cntr=0.3,0.1