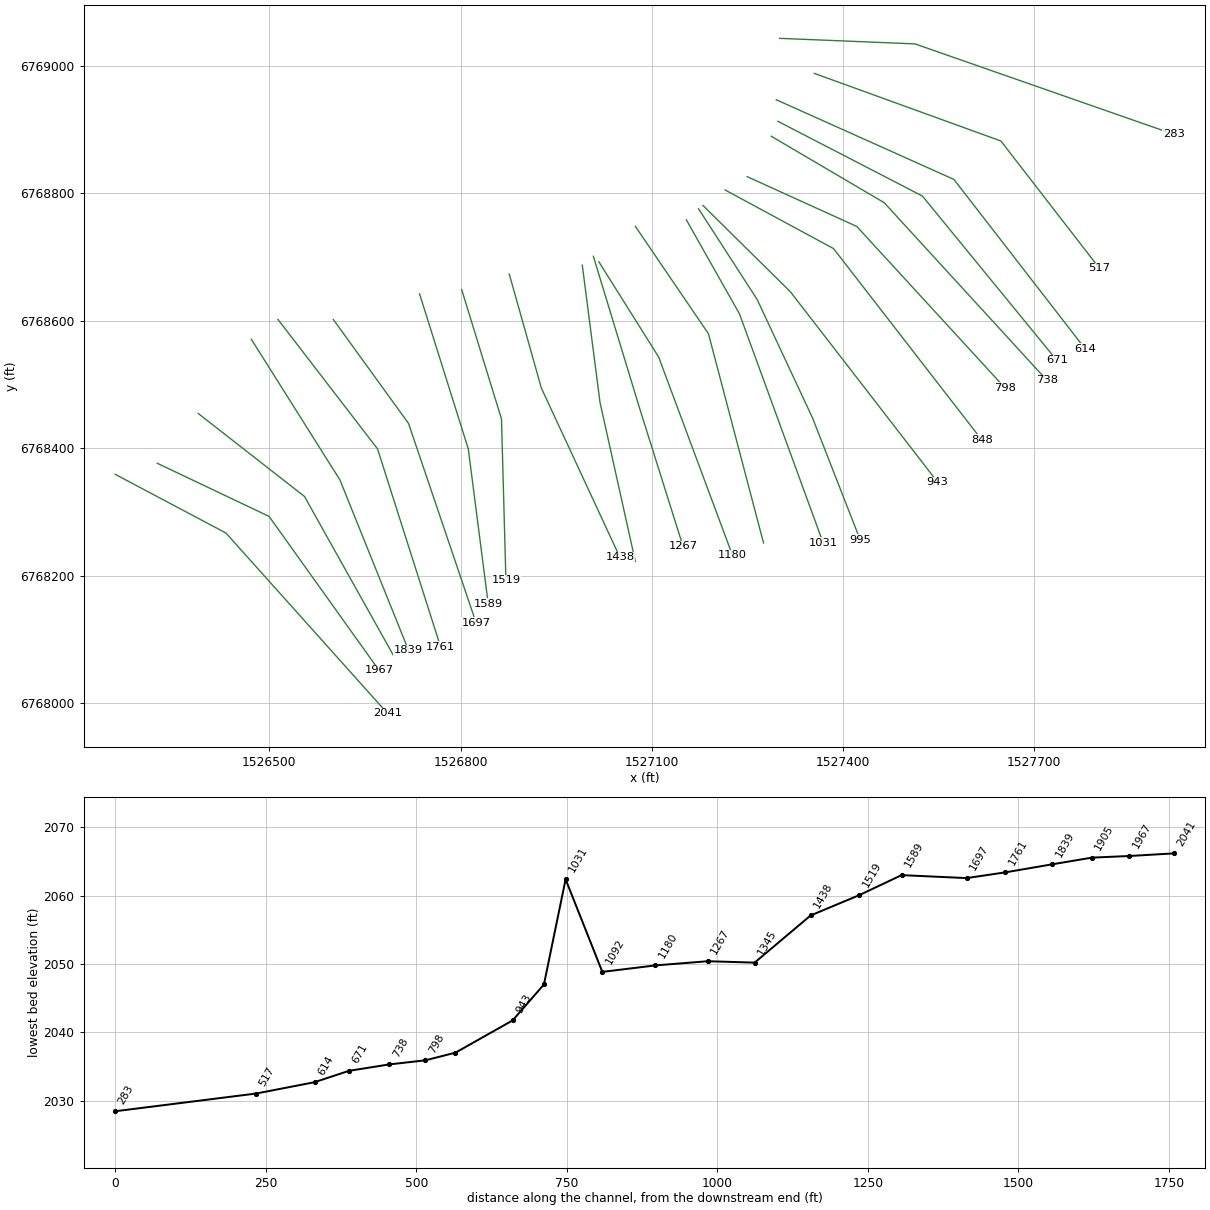
HEC-RAS study Elm 68.prj: Elm 68 Base Level Engineering

--- Elm 68.g01 (geometry) --- (continued)

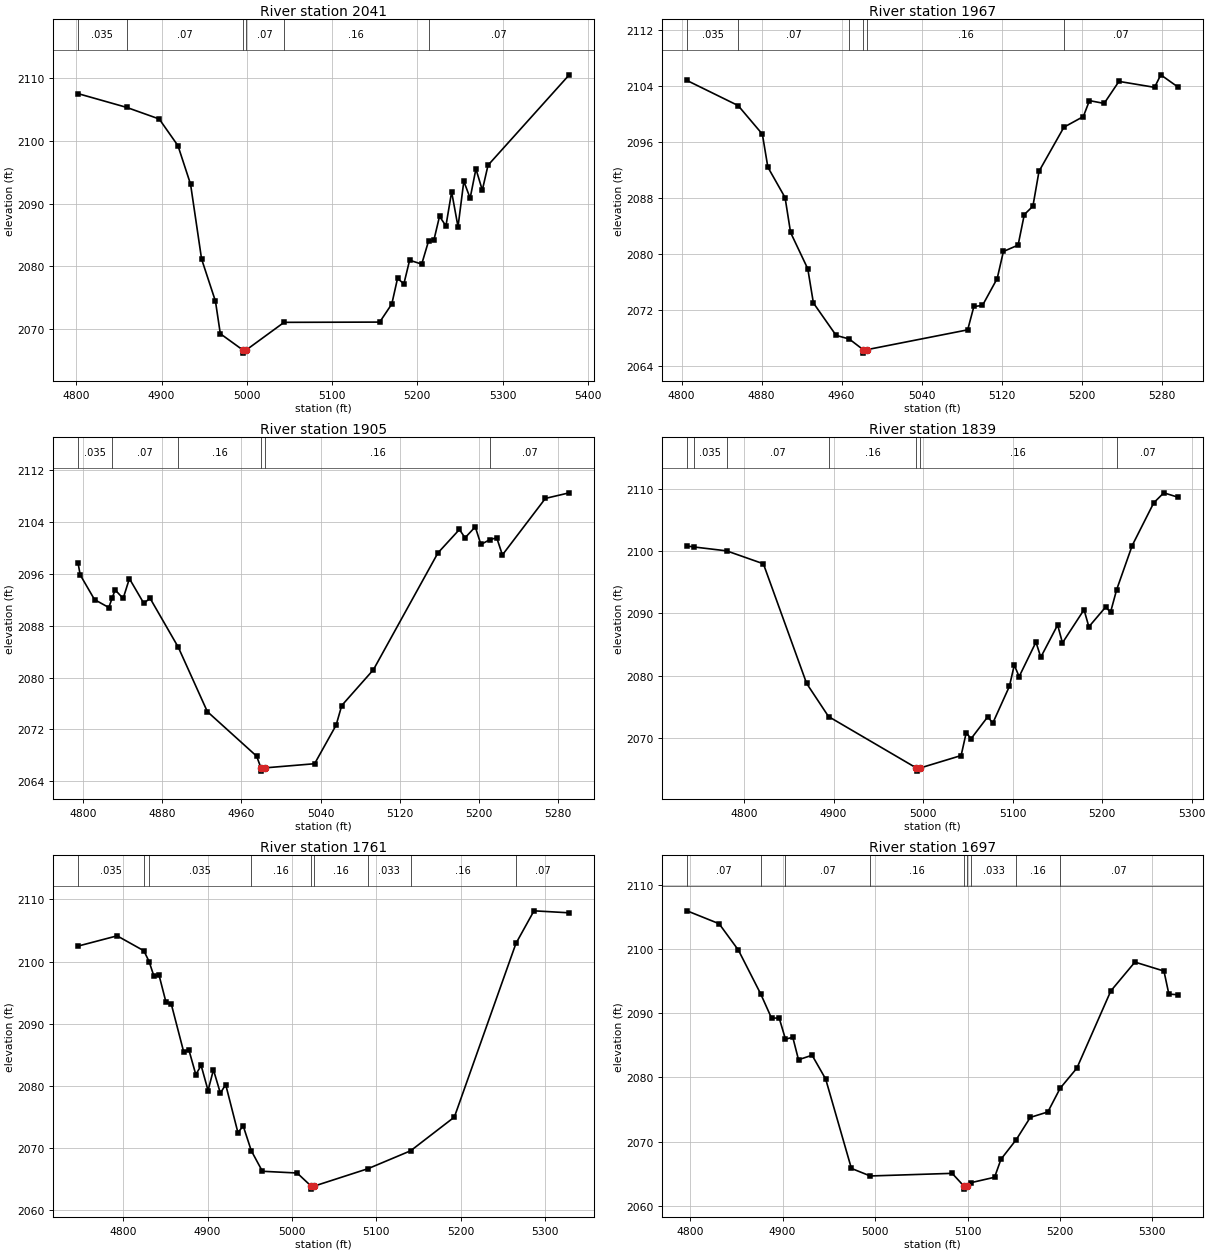
Type RM Length L Ch R = 1,2041,74,74,74
BEGIN DESCRIPTION:
Elm 68 2041.07
END DESCRIPTION:
XS GIS Cut Line= 3
      1526258.31      6768359.00      1526431.91      6768266.99
      1526685.40      6767983.99
#Sta/Elev= 30
  4801.9 2107.51  4858.9 2105.32  4897.2 2103.47  4919.2 2099.22  4934.0 2093.08
  4946.9 2081.19  4963.2 2074.46  4968.9 2069.29  4995.3 2066.70  4995.5 2066.20
  4999.3 2066.70  5043.7 2071.10  5155.9 2071.14  5170.1 2074.02  5176.8 2078.08
  5184.3 2077.24  5191.0 2080.99  5205.2 2080.37  5213.3 2084.08  5219.4 2084.14
  5226.1 2087.98  5233.6 2086.44  5240.3 2091.87  5247.8 2086.31  5254.6 2093.57
  5262.0 2090.86  5268.8 2095.52  5276.3 2092.14  5283.0 2096.11  5378.3 2110.50
#Mann=6,-1,0
  4801.9   0.035       0  4858.9    0.07       0  4995.3    0.07       0
  4999.3    0.07       0  5043.7    0.16       0  5213.3    0.07       0
Bank Sta=4995.3,4999.3
Exp/Cntr=0.3,0.1

Type RM Length L Ch R = 1,1967,62,62,62
BEGIN DESCRIPTION:
Elm 68 1966.88
END DESCRIPTION:
XS GIS Cut Line= 3
      1526324.25      6768376.38      1526499.62      6768293.03
      1526672.15      6768051.49
#Sta/Elev= 30
  4805.5 2104.82  4856.6 2101.23  4880.8 2097.14  4886.3 2092.42  4903.5 2088.07
  4909.0 2083.08  4926.2 2077.88  4931.8 2073.00  4954.5 2068.36  4967.6 2067.84
  4981.5 2066.32  4981.7 2065.82  4985.5 2066.32  5086.0 2069.15  5092.2 2072.49
  5100.8 2072.64  5115.5 2076.49  5121.7 2080.36  5136.4 2081.27  5142.6 2085.64
  5151.2 2086.84  5157.3 2091.83  5182.2 2098.14  5201.6 2099.66  5207.7 2101.94
  5222.4 2101.54  5237.2 2104.69  5272.8 2103.84  5279.0 2105.63  5296.5 2103.85
#Mann=6,-1,0
  4805.5   0.035       0  4856.6    0.07       0  4967.6    0.16       0
  4981.5    0.07       0  4985.5    0.16       0  5182.2    0.07       0
Bank Sta=4981.5,4985.5
Exp/Cntr=0.3,0.1

Type RM Length L Ch R = 1,1905,66,66,66
BEGIN DESCRIPTION:
Elm 68 1904.6
END DESCRIPTION:
XS GIS Cut Line= 3
      1526388.47      6768454.52      1526555.17      6768324.28
      1526694.06      6768076.03
#Sta/Elev= 30
  4795.1 2097.72  4797.3 2095.83  4811.8 2092.01  4826.2 2090.79  4829.7 2092.28
  4832.6 2093.51  4840.7 2092.18  4847.0 2095.24  4861.5 2091.45  4867.9 2092.21
  4896.4 2084.66  4925.7 2074.75  4975.5 2067.88  4979.8 2066.08  4980.1 2065.58
  4983.8 2066.08  5034.0 2066.72  5055.7 2072.66  5061.4 2075.69  5093.4 2081.21
  5158.5 2099.20  5180.2 2102.81  5185.9 2101.53  5196.2 2103.22  5201.9 2100.50
  5211.1 2101.26  5217.9 2101.52  5223.6 2098.89  5267.0 2107.60  5291.1 2108.46
#Mann=6,-1,0
  4795.1   0.035       0  4829.7    0.07       0  4896.4    0.16       0
  4979.8    0.07       0  4983.8    0.16       0  5211.1    0.07       0
Bank Sta=4979.8,4983.8
Exp/Cntr=0.3,0.1

Type RM Length L Ch R = 1,1839,78,78,78
BEGIN DESCRIPTION:
Elm 68 1838.52
END DESCRIPTION:
XS GIS Cut Line= 3
      1526471.83      6768570.83      1526610.73      6768350.33
      1526718.36      6768082.99
#Sta/Elev= 30
  4736.3 2100.87  4743.9 2100.71  4780.6 2100.08  4821.6 2098.00  4869.9 2078.73
  4894.4 2073.39  4992.6 2065.10  4992.9 2064.60  4996.6 2065.10  5042.5 2067.11
  5048.2 2070.79  5053.6 2069.82  5072.4 2073.38  5077.8 2072.31  5096.4 2078.25
  5101.9 2081.68  5107.3 2079.82  5126.1 2085.38  5131.5 2082.95  5150.3 2088.14
  5155.7 2085.26  5179.8 2090.60  5185.2 2087.85  5204.0 2091.04  5209.4 2090.18
  5216.2 2093.81  5233.6 2100.94  5257.7 2107.82  5268.9 2109.43  5285.1 2108.71
#Mann=7,-1,0
  4736.3    0.07       0  4743.9   0.035       0  4780.6    0.07       0
  4894.4    0.16       0  4992.6    0.07       0  4996.6    0.16       0
  5216.2    0.07       0
Bank Sta=4992.6,4996.6
Exp/Cntr=0.3,0.1

Type RM Length L Ch R = 1,1761,64,64,64
BEGIN DESCRIPTION:
Elm 68 1760.73
END DESCRIPTION:
XS GIS Cut Line= 3
      1526513.50      6768602.07      1526669.76      6768398.94
      1526768.71      6768088.19
#Sta/Elev= 30
  4746.4 2102.48  4792.8 2104.13  4824.5 2101.73  4830.7 2100.00  4836.3 2097.70
  4842.6 2097.76  4850.8 2093.42  4857.1 2093.12  4871.6 2085.54  4877.9 2085.78
  4886.1 2081.83  4892.4 2083.30  4900.6 2079.27  4907.0 2082.60  4915.2 2078.84
  4921.5 2080.23  4936.0 2072.51  4942.3 2073.57  4951.8 2069.61  4965.0 2066.29
  5006.2 2066.01  5022.7 2063.92  5022.9 2063.42  5026.7 2063.92  5090.3 2066.71
  5140.7 2069.58  5192.6 2075.00  5265.6 2102.91  5287.0 2108.15  5328.8 2107.83
#Mann=9,-1,0
  4746.4   0.035       0  4824.5    0.07       0  4830.7   0.035       0
  4951.8    0.16       0  5022.7    0.07       0  5026.7    0.16       0
  5090.3   0.033       0  5140.7    0.16       0  5265.6    0.07       0
Bank Sta=5022.7,5026.7
Exp/Cntr=0.3,0.1

Type RM Length L Ch R = 1,1697,108,108,108
BEGIN DESCRIPTION:
Elm 68 1696.76
END DESCRIPTION:
XS GIS Cut Line= 3
      1526600.32      6768602.05      1526718.37      6768438.87
      1526824.28      6768126.33
#Sta/Elev= 30
  4796.6 2105.97  4831.3 2103.96  4852.2 2099.84  4876.3 2093.02  4888.0 2089.25
  4896.3 2089.26  4903.1 2085.96  4911.0 2086.26  4917.2 2082.76  4931.9 2083.46
  4946.6 2079.74  4974.4 2065.82  4994.8 2064.64  5083.4 2065.05  5095.9 2063.09
  5096.1 2062.59  5099.9 2063.09  5103.6 2063.59  5129.3 2064.44  5136.2 2067.25
  5152.7 2070.30  5167.9 2073.77  5186.9 2074.62  5200.2 2078.31  5218.3 2081.45
  5255.0 2093.48  5281.1 2097.98  5312.5 2096.58  5317.8 2092.99  5328.0 2092.89
#Mann=9,-1,0
  4796.6    0.07       0  4876.3   0.035       0  4903.1    0.07       0
  4994.8    0.16       0  5095.9    0.07       0  5099.9    0.16       0
  5103.6   0.033       0  5152.7    0.16       0  5200.2    0.07       0
Bank Sta=5095.9,5099.9
Exp/Cntr=0.3,0.1

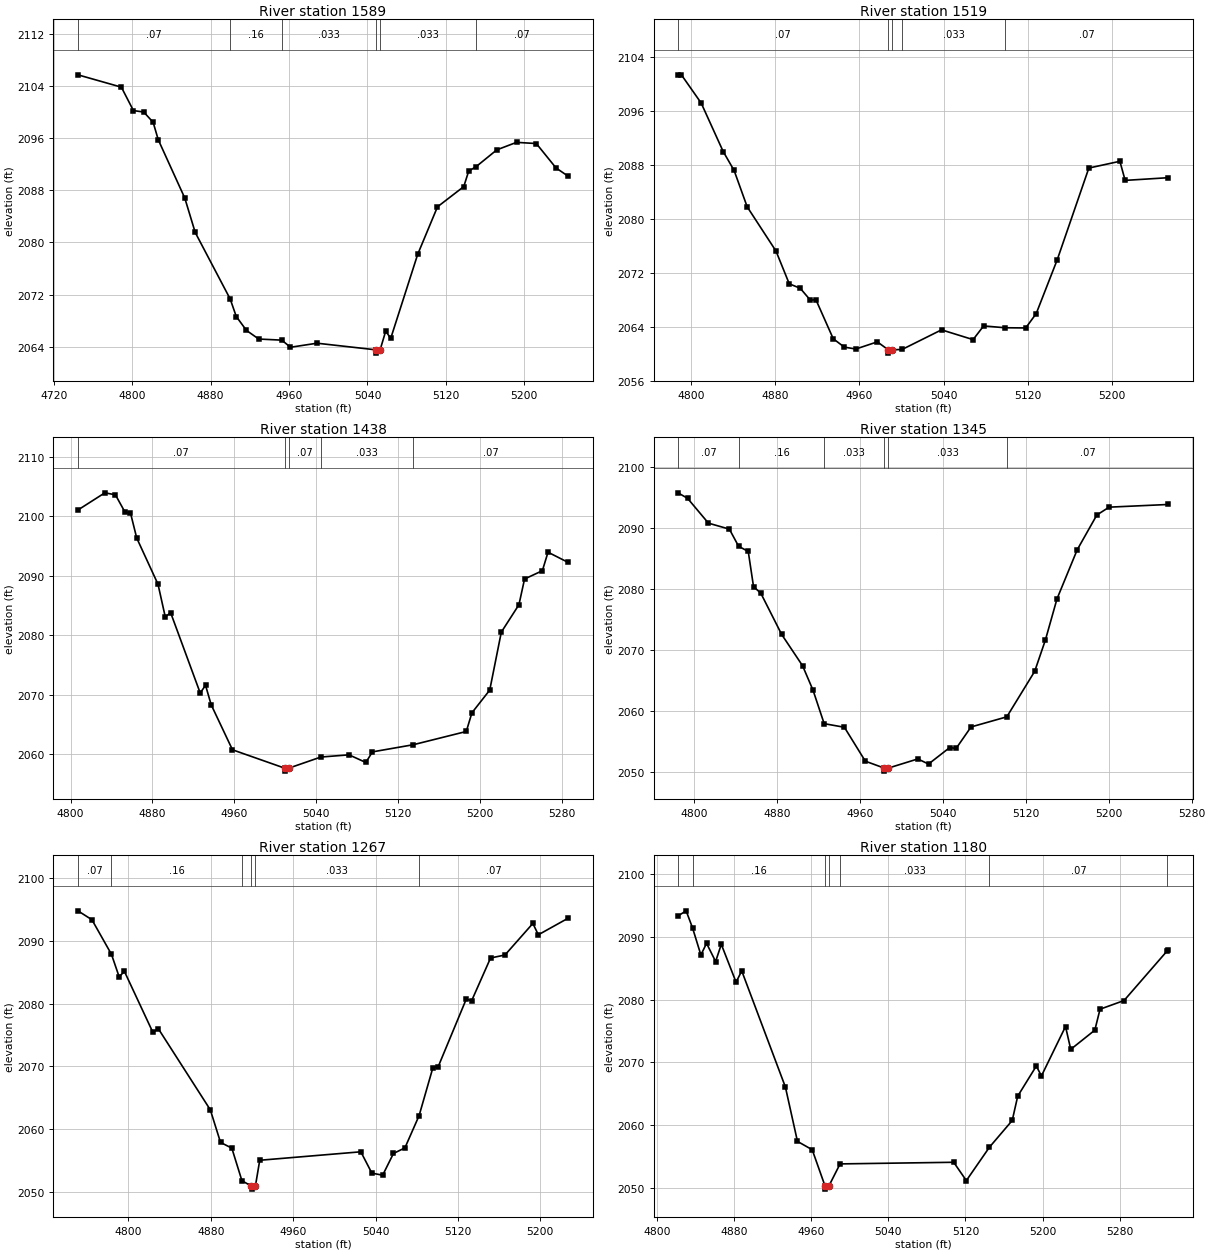
Type RM Length L Ch R = 1,1589,70,70,70
BEGIN DESCRIPTION:
Elm 68 1589.13
END DESCRIPTION:
XS GIS Cut Line= 3
      1526735.72      6768642.03      1526812.12      6768398.94
      1526843.37      6768155.85
#Sta/Elev= 30
  4744.7 2105.67  4789.0 2103.78  4801.3 2100.19  4811.8 2099.97  4821.4 2098.40
  4826.6 2095.73  4853.7 2086.78  4864.3 2081.52  4900.0 2071.31  4906.2 2068.63
  4916.6 2066.50  4929.1 2065.18  4952.6 2065.01  4961.5 2063.92  4988.6 2064.54
  5048.9 2063.52  5049.1 2063.02  5052.9 2063.52  5058.6 2066.40  5063.7 2065.27
  5091.2 2078.15  5111.4 2085.44  5138.2 2088.54  5143.2 2090.90  5151.0 2091.62
  5171.9 2094.17  5192.0 2095.32  5212.2 2095.14  5232.3 2091.40  5244.6 2090.14
#Mann=6,-1,0
  4744.7    0.07       0  4900.0    0.16       0  4952.6   0.033       0
  5048.9   0.033       0  5052.9   0.033       0  5151.0    0.07       0
Bank Sta=5048.9,5052.9
Exp/Cntr=0.3,0.1

Type RM Length L Ch R = 1,1519,81,81,81
BEGIN DESCRIPTION:
Elm 68 1518.53
END DESCRIPTION:
XS GIS Cut Line= 3
      1526801.69      6768648.98      1526864.20      6768445.81
      1526871.14      6768192.68
#Sta/Elev= 30
  4787.6 2101.33  4790.8 2101.33  4809.6 2097.15  4830.5 2089.97  4840.9 2087.16
  4853.3 2081.78  4880.7 2075.22  4893.3 2070.37  4903.7 2069.71  4913.4 2067.94
  4918.6 2068.03  4935.1 2062.23  4945.6 2060.99  4956.6 2060.71  4977.0 2061.77
  4987.3 2060.60  4987.5 2060.10  4991.3 2060.60  5000.5 2060.64  5038.0 2063.55
  5068.0 2062.10  5078.0 2064.13  5098.3 2063.86  5118.0 2063.83  5128.0 2065.96
  5148.0 2073.95  5178.0 2087.52  5207.5 2088.52  5212.5 2085.69  5253.4 2086.09
#Mann=5,-1,0
  4787.6    0.07       0  4987.3    0.07       0  4991.3    0.07       0
  5000.5   0.033       0  5098.3    0.07       0
Bank Sta=4987.3,4991.3
Exp/Cntr=0.3,0.1

Type RM Length L Ch R = 1,1438,93,93,93
BEGIN DESCRIPTION:
Elm 68 1437.54
END DESCRIPTION:
XS GIS Cut Line= 3
      1526876.35      6768673.27      1526926.70      6768494.42
      1527049.95      6768228.83
#Sta/Elev= 30
  4807.2 2101.05  4833.5 2103.94  4843.8 2103.61  4853.3 2100.65  4858.5 2100.57
  4864.6 2096.34  4885.4 2088.56  4892.5 2083.05  4897.7 2083.79  4926.6 2070.26
  4931.8 2071.56  4937.3 2068.29  4958.1 2060.71  5009.1 2057.62  5009.4 2057.12
  5013.1 2057.62  5044.4 2059.49  5071.9 2059.86  5088.3 2058.58  5094.8 2060.36
  5134.6 2061.56  5186.4 2063.79  5191.9 2066.93  5209.3 2070.75  5220.6 2080.50
  5237.8 2085.11  5243.3 2089.44  5260.7 2090.84  5266.2 2093.95  5285.8 2092.24
#Mann=5,-1,0
  4807.2    0.07       0  5009.1    0.07       0  5013.1    0.07       0
  5044.4   0.033       0  5134.6    0.07       0
Bank Sta=5009.1,5013.1
Exp/Cntr=0.3,0.1

Type RM Length L Ch R = 1,1345,78,78,78
BEGIN DESCRIPTION:
Elm 68 1345.07
END DESCRIPTION:
XS GIS Cut Line= 3
      1526990.94      6768687.11      1527018.72      6768471.85
      1527074.15      6768222.38
#Sta/Elev= 30
  4784.7 2095.84  4793.9 2094.94  4814.0 2090.87  4834.2 2089.89  4843.1 2087.08
  4852.4 2086.23  4857.5 2080.46  4864.5 2079.39  4884.6 2072.63  4904.8 2067.49
  4914.9 2063.47  4925.6 2058.00  4945.1 2057.41  4965.3 2051.85  4983.5 2050.72
  4983.7 2050.22  4987.5 2050.72  5015.9 2052.22  5026.2 2051.38  5046.7 2054.09
  5052.8 2053.93  5067.2 2057.46  5101.7 2059.12  5128.6 2066.58  5138.9 2071.71
  5150.1 2078.46  5169.6 2086.51  5188.5 2092.20  5200.3 2093.49  5257.3 2093.93
#Mann=6,-1,0
  4784.7    0.07       0  4843.1    0.16       0  4925.6   0.033       0
  4983.5   0.033       0  4987.5   0.033       0  5101.7    0.07       0
Bank Sta=4983.5,4987.5
Exp/Cntr=0.3,0.1

Type RM Length L Ch R = 1,1267,87,87,87
BEGIN DESCRIPTION:
Elm 68 1267.09
END DESCRIPTION:
XS GIS Cut Line= 3
      1527008.29      6768701.04      1527081.22      6768461.44
      1527148.92      6768246.18
#Sta/Elev= 30
  4750.9 2094.78  4764.5 2093.36  4783.5 2087.84  4790.9 2084.28  4796.1 2085.11
  4823.7 2075.41  4829.0 2075.99  4879.5 2063.06  4889.4 2057.87  4900.4 2056.95
  4910.2 2051.76  4919.3 2050.92  4919.6 2050.42  4923.3 2050.92  4927.5 2055.02
  5025.7 2056.37  5036.4 2052.97  5046.9 2052.64  5057.4 2056.11  5068.5 2056.99
  5082.3 2062.14  5095.7 2069.79  5100.9 2069.96  5128.1 2080.71  5133.3 2080.44
  5151.7 2087.26  5165.7 2087.74  5192.8 2092.77  5198.1 2090.96  5227.0 2093.60
#Mann=6,-1,0
  4750.9    0.07       0  4783.5    0.16       0  4910.2   0.033       0
  4919.3   0.033       0  4923.3   0.033       0  5082.3    0.07       0
Bank Sta=4919.3,4923.3
Exp/Cntr=0.3,0.1

Type RM Length L Ch R = 1,1180,88,88,88
BEGIN DESCRIPTION:
Elm 68 1180.42
END DESCRIPTION:
XS GIS Cut Line= 3
      1527016.96      6768692.38      1527110.73      6768543.03
      1527226.60      6768231.74
#Sta/Elev= 30
  4821.8 2093.36  4830.2 2094.17  4836.9 2091.43  4845.5 2087.14  4851.4 2088.99
  4860.8 2086.09  4866.7 2088.83  4882.0 2082.80  4887.9 2084.59  4933.2 2066.08
  4945.7 2057.42  4961.0 2056.09  4974.3 2050.31  4974.5 2049.81  4978.3 2050.31
  4989.9 2053.83  5107.8 2054.09  5120.9 2051.17  5144.9 2056.50  5168.5 2060.75
  5174.2 2064.63  5193.5 2069.43  5198.8 2067.85  5223.8 2075.73  5229.2 2072.09
  5254.2 2075.15  5259.6 2078.49  5284.5 2079.87  5329.3 2087.79  5330.3 2087.97
#Mann=7,-1,0
  4821.8    0.07       0  4836.9    0.16       0  4974.3   0.033       0
  4978.3    0.16       0  4989.9   0.033       0  5144.9    0.07       0
  5329.3   0.035       0
Bank Sta=4974.3,4978.3
Exp/Cntr=0.3,0.1

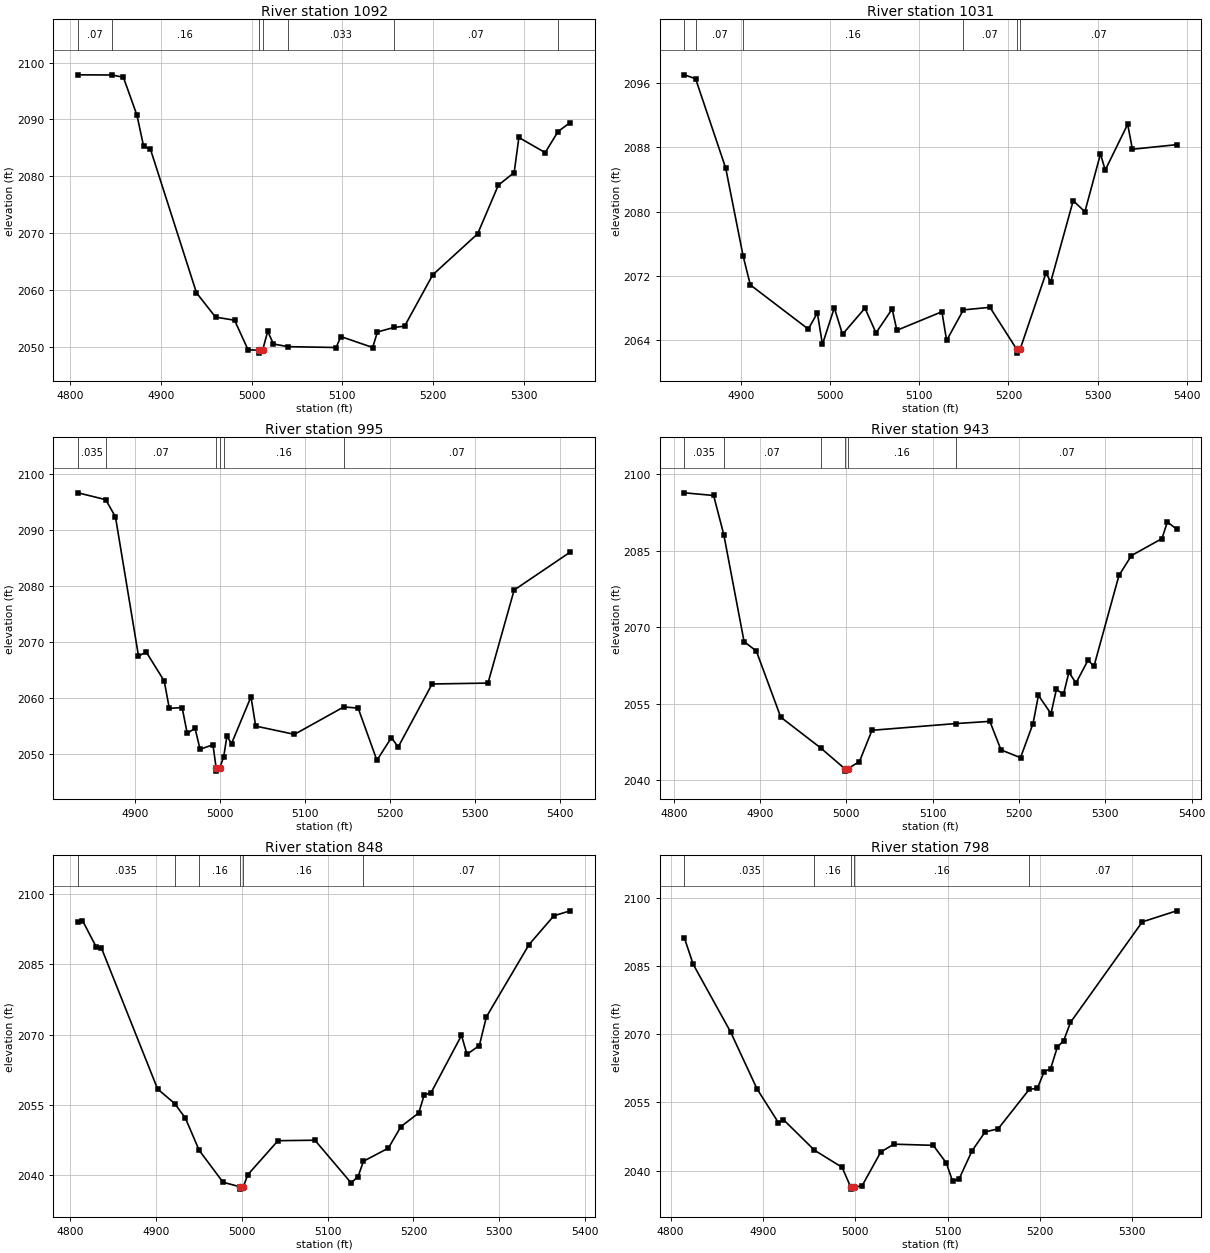
Type RM Length L Ch R = 1,1092,61,61,61
BEGIN DESCRIPTION:
Elm 68 1091.53
END DESCRIPTION:
XS GIS Cut Line= 3
      1527074.27      6768747.89      1527188.85      6768579.49
      1527275.21      6768251.35
#Sta/Elev= 30
  4808.4 2097.84  4845.5 2097.81  4858.4 2097.43  4873.4 2090.74  4880.8 2085.23
  4888.3 2084.75  4939.1 2059.47  4960.1 2055.20  4981.1 2054.65  4996.0 2049.45
  5008.0 2049.36  5008.2 2048.86  5012.0 2049.36  5017.7 2052.70  5024.0 2050.47
  5040.0 2050.00  5093.2 2049.85  5098.3 2051.78  5133.5 2049.85  5138.7 2052.58
  5157.2 2053.39  5168.7 2053.60  5199.8 2062.65  5249.3 2069.86  5272.1 2078.41
  5289.6 2080.64  5294.8 2086.81  5323.8 2084.15  5338.0 2087.86  5351.4 2089.44
#Mann=7,-1,0
  4808.4    0.07       0  4845.5    0.16       0  5008.0    0.07       0
  5012.0    0.16       0  5040.0   0.033       0  5157.2    0.07       0
  5338.0   0.035       0
Bank Sta=5008,5012
Exp/Cntr=0.3,0.1

Type RM Length L Ch R = 1,1031,36,36,36
BEGIN DESCRIPTION:
Elm 68 1030.99
END DESCRIPTION:
XS GIS Cut Line= 3
      1527154.15      6768758.28      1527237.47      6768610.74
      1527368.79      6768251.32
#Sta/Elev= 30
  4836.6 2097.04  4849.1 2096.55  4882.9 2085.42  4902.4 2074.50  4910.5 2070.90
  4975.5 2065.40  4985.7 2067.41  4991.4 2063.50  5004.7 2068.05  5013.9 2064.75
  5039.1 2068.01  5051.5 2064.93  5069.6 2067.90  5074.9 2065.25  5125.4 2067.56
  5130.7 2063.99  5149.5 2067.79  5179.3 2068.11  5209.2 2062.91  5209.5 2062.41
  5213.2 2062.91  5242.2 2072.38  5247.5 2071.27  5272.7 2081.38  5285.8 2080.00
  5303.3 2087.20  5308.6 2085.18  5333.8 2090.89  5339.1 2087.78  5388.7 2088.35
#Mann=6,-1,0
  4836.6   0.035       0  4849.1    0.07       0  4902.4    0.16       0
  5149.5    0.07       0  5209.2    0.07       0  5213.2    0.07       0
Bank Sta=5209.2,5213.2
Exp/Cntr=0.3,0.1

Type RM Length L Ch R = 1,995,52,52,52
BEGIN DESCRIPTION:
Elm 68 995.1
END DESCRIPTION:
XS GIS Cut Line= 4
      1527173.23      6768775.67      1527265.24      6768633.31
      1527352.05      6768447.55      1527426.70      6768256.57
#Sta/Elev= 30
  4832.8 2096.68  4865.4 2095.46  4876.9 2092.38  4904.0 2067.57  4913.2 2068.25
  4934.3 2063.11  4940.3 2058.22  4955.4 2058.36  4961.4 2053.77  4970.6 2054.67
  4976.5 2050.92  4991.7 2051.72  4995.5 2047.52  4995.7 2047.02  4999.5 2047.52
  5004.4 2049.59  5008.1 2053.24  5013.6 2051.94  5036.5 2060.28  5042.0 2055.06
  5087.7 2053.58  5145.8 2058.48  5162.7 2058.26  5184.8 2048.95  5201.9 2053.01
  5209.8 2051.31  5249.8 2062.57  5315.6 2062.73  5346.4 2079.33  5412.4 2086.10
#Mann=6,-1,0
  4832.8   0.035       0  4865.4    0.07       0  4995.5    0.07       0
  4999.5    0.07       0  5004.4    0.16       0  5145.8    0.07       0
Bank Sta=4995.5,4999.5
Exp/Cntr=0.3,0.1

Type RM Length L Ch R = 1,943,95,95,95
BEGIN DESCRIPTION:
Elm 68 942.69
END DESCRIPTION:
XS GIS Cut Line= 3
      1527180.14      6768780.91      1527317.33      6768645.46
      1527548.26      6768346.82
#Sta/Elev= 30
  4812.3 2096.34  4846.1 2095.82  4857.9 2088.13  4881.4 2067.16  4895.6 2065.31
  4923.9 2052.34  4970.2 2046.30  4997.9 2042.26  4998.2 2041.76  5001.9 2042.26
  5015.1 2043.64  5029.6 2049.77  5127.0 2051.09  5166.2 2051.52  5179.1 2045.93
  5201.7 2044.39  5216.2 2051.07  5222.5 2056.62  5237.0 2053.02  5243.3 2057.79
  5251.5 2056.80  5257.8 2061.16  5266.0 2059.03  5280.0 2063.54  5286.8 2062.32
  5315.8 2080.14  5330.3 2084.04  5365.6 2087.36  5371.9 2090.63  5382.6 2089.22
#Mann=6,-1,0
  4812.3   0.035       0  4857.9    0.07       0  4970.2    0.16       0
  4997.9    0.07       0  5001.9    0.16       0  5127.0    0.07       0
Bank Sta=4997.9,5001.9
Exp/Cntr=0.3,0.1

Type RM Length L Ch R = 1,848,50,50,50
BEGIN DESCRIPTION:
Elm 68 847.61
END DESCRIPTION:
XS GIS Cut Line= 3
      1527214.88      6768805.19      1527385.03      6768713.17
      1527617.58      6768412.94
#Sta/Elev= 30
  4809.4 2094.15  4814.6 2094.38  4830.8 2088.66  4836.5 2088.59  4902.1 2058.41
  4922.0 2055.31  4934.5 2052.18  4950.5 2045.32  4978.3 2038.51  4998.0 2037.54
  4998.2 2037.04  5002.0 2037.54  5007.0 2040.09  5042.3 2047.38  5085.3 2047.48
  5127.4 2038.38  5135.6 2039.72  5141.8 2042.99  5170.9 2045.80  5185.4 2050.38
  5206.2 2053.29  5212.5 2057.10  5220.7 2057.66  5256.0 2069.86  5262.4 2065.82
  5276.8 2067.69  5285.0 2073.81  5334.7 2089.25  5363.6 2095.39  5382.6 2096.45
#Mann=6,-1,0
  4809.4   0.035       0  4922.0    0.07       0  4950.5    0.16       0
  4998.0    0.07       0  5002.0    0.16       0  5141.8    0.07       0
Bank Sta=4998,5002
Exp/Cntr=0.3,0.1

Type RM Length L Ch R = 1,798,60,60,60
BEGIN DESCRIPTION:
Elm 68 797.85
END DESCRIPTION:
XS GIS Cut Line= 3
      1527249.58      6768826.04      1527421.49      6768747.89
      1527654.14      6768494.42
#Sta/Elev= 30
  4815.1 2091.19  4824.5 2085.45  4865.0 2070.55  4893.7 2057.98  4916.8 2050.58
  4922.3 2051.21  4955.9 2044.48  4985.8 2040.72  4995.0 2036.42  4995.2 2035.92
  4999.0 2036.42  5007.3 2036.60  5027.7 2044.10  5041.9 2045.82  5084.5 2045.56
  5098.6 2041.70  5105.4 2037.68  5112.4 2038.12  5126.4 2044.32  5140.6 2048.50
  5154.8 2049.21  5188.4 2057.88  5197.3 2058.15  5204.7 2061.82  5211.5 2062.40
  5218.9 2067.22  5225.7 2068.59  5233.1 2072.64  5310.8 2094.76  5348.0 2097.20
#Mann=5,-1,0
  4815.1   0.035       0  4955.9    0.16       0  4995.0    0.07       0
  4999.0    0.16       0  5188.4    0.07       0
Bank Sta=4995,4999
Exp/Cntr=0.3,0.1

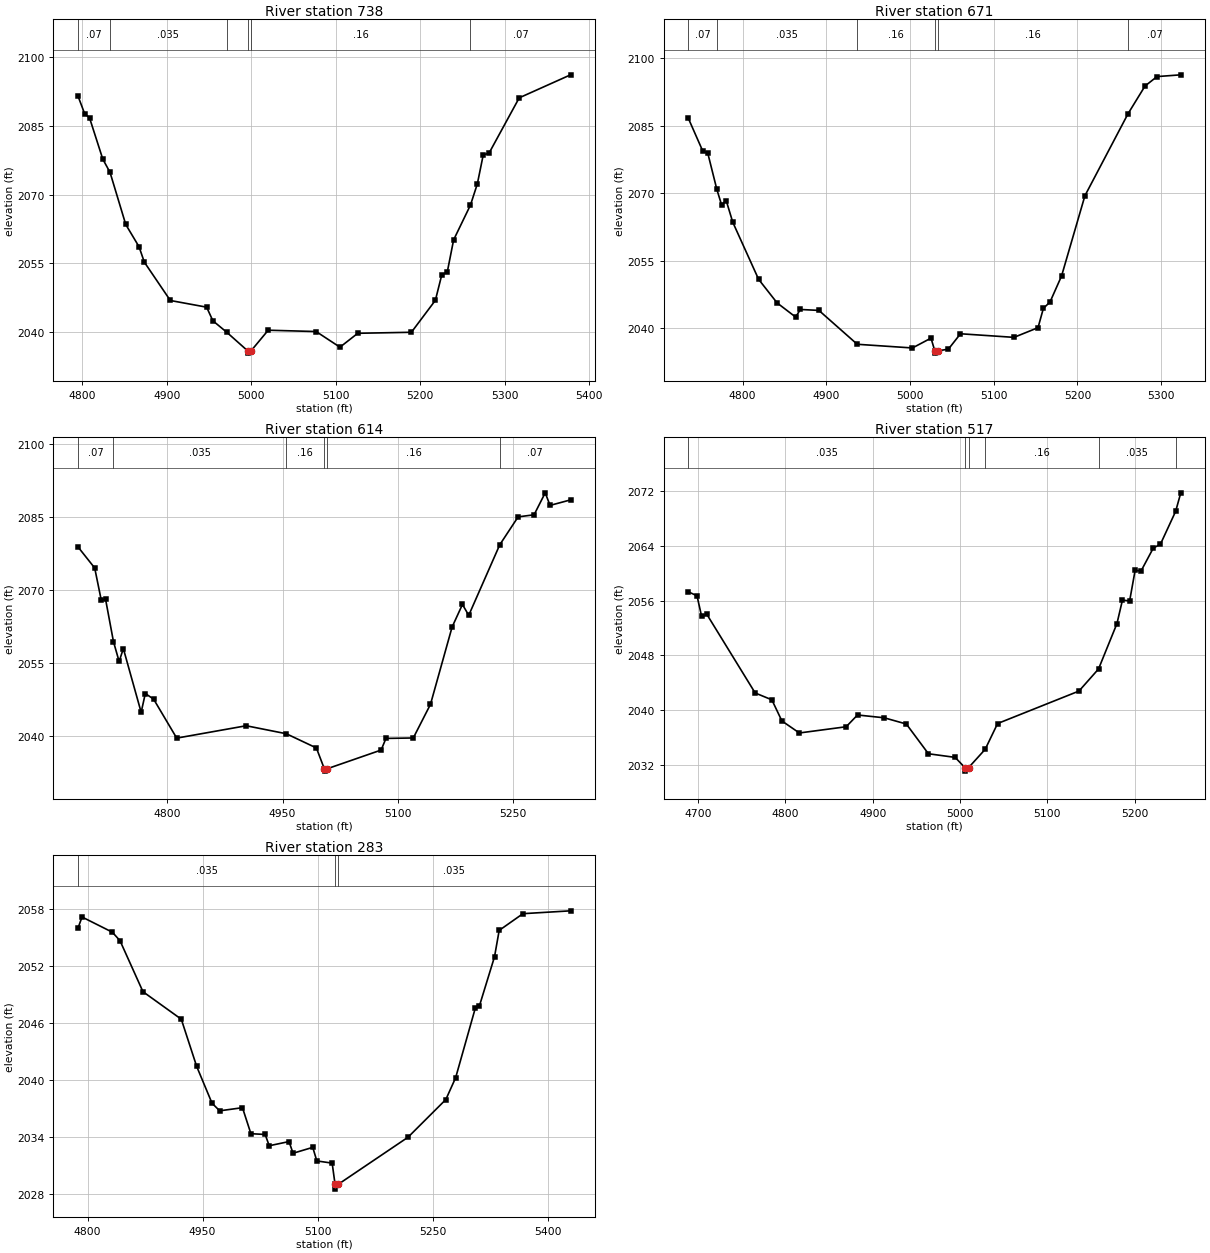
Type RM Length L Ch R = 1,738,67,67,67
BEGIN DESCRIPTION:
Elm 68 738.13
END DESCRIPTION:
XS GIS Cut Line= 3
      1527287.38      6768889.39      1527464.46      6768785.22
      1527719.67      6768506.58
#Sta/Elev= 30
  4794.9 2091.51  4802.7 2087.69  4808.5 2086.78  4824.2 2077.75  4832.8 2074.84
  4851.4 2063.45  4867.1 2058.60  4873.4 2055.22  4904.2 2046.83  4947.2 2045.37
  4954.6 2042.39  4971.0 2039.89  4995.8 2035.82  4996.0 2035.32  4999.8 2035.82
  5020.1 2040.33  5076.9 2040.04  5105.1 2036.62  5126.2 2039.66  5189.7 2039.88
  5218.1 2046.87  5225.5 2052.31  5232.3 2053.15  5239.7 2060.08  5259.7 2067.72
  5267.8 2072.33  5274.8 2078.68  5281.6 2079.03  5317.4 2091.15  5378.2 2096.18
#Mann=6,-1,0
  4794.9    0.07       0  4832.8   0.035       0  4971.0    0.16       0
  4995.8    0.07       0  4999.8    0.16       0  5259.7    0.07       0
Bank Sta=4995.8,4999.8
Exp/Cntr=0.3,0.1

Type RM Length L Ch R = 1,671,57,57,57
BEGIN DESCRIPTION:
Elm 68 671.41
END DESCRIPTION:
XS GIS Cut Line= 3
      1527297.82      6768912.81      1527524.36      6768795.64
      1527735.33      6768537.79
#Sta/Elev= 30
  4735.2 2086.69  4752.7 2079.28  4758.4 2078.97  4769.3 2070.84  4774.9 2067.44
  4780.5 2068.34  4788.3 2063.54  4819.2 2050.81  4841.3 2045.56  4863.4 2042.41
  4869.1 2044.10  4891.2 2043.89  4937.0 2036.35  5002.9 2035.53  5025.1 2037.72
  5029.6 2034.88  5029.8 2034.38  5033.6 2034.88  5045.9 2035.28  5060.3 2038.69
  5124.2 2037.89  5152.9 2040.05  5159.3 2044.35  5167.2 2045.76  5181.0 2051.55
  5208.9 2069.42  5260.3 2087.65  5280.7 2093.85  5295.0 2095.95  5323.4 2096.34
#Mann=6,-1,0
  4735.2    0.07       0  4769.3   0.035       0  4937.0    0.16       0
  5029.6    0.07       0  5033.6    0.16       0  5260.3    0.07       0
Bank Sta=5029.6,5033.6
Exp/Cntr=0.3,0.1

Type RM Length L Ch R = 1,614,97,97,97
BEGIN DESCRIPTION:
Elm 68 613.51
END DESCRIPTION:
XS GIS Cut Line= 3
      1527295.18      6768946.69      1527573.84      6768821.68
      1527779.57      6768556.05
#Sta/Elev= 30
  4683.7 2078.76  4705.4 2074.44  4714.0 2067.78  4719.5 2068.06  4729.8 2059.34
  4737.2 2055.24  4742.7 2057.89  4765.9 2044.80  4771.3 2048.66  4782.1 2047.51
  4812.2 2039.50  4902.7 2042.04  4954.9 2040.40  4994.1 2037.48  5004.4 2033.22
  5004.7 2032.72  5008.4 2033.22  5078.4 2037.05  5084.7 2039.44  5120.3 2039.53
  5142.7 2046.45  5170.8 2062.30  5184.3 2066.95  5192.5 2064.72  5232.9 2079.21
  5256.8 2084.94  5277.6 2085.37  5292.1 2089.88  5298.4 2087.30  5325.1 2088.43
#Mann=6,-1,0
  4683.7    0.07       0  4729.8   0.035       0  4954.9    0.16       0
  5004.4    0.07       0  5008.4    0.16       0  5232.9    0.07       0
Bank Sta=5004.4,5008.4
Exp/Cntr=0.3,0.1

Type RM Length L Ch R = 1,517,234,234,234
BEGIN DESCRIPTION:
Elm 68 517.345
END DESCRIPTION:
XS GIS Cut Line= 3
      1527354.98      6768988.01      1527647.55      6768881.95
      1527802.26      6768682.02
#Sta/Elev= 30
  4688.8 2057.29  4698.8 2056.70  4704.1 2053.68  4710.1 2053.98  4765.4 2042.49
  4784.5 2041.49  4796.0 2038.40  4816.0 2036.64  4869.6 2037.55  4882.6 2039.27
  4913.2 2038.86  4938.5 2037.95  4963.8 2033.60  4994.4 2033.07  5005.7 2031.56
  5005.9 2031.06  5009.7 2031.56  5028.8 2034.25  5043.0 2038.02  5136.2 2042.77
  5158.6 2046.00  5179.7 2052.64  5186.0 2056.08  5194.2 2055.94  5200.5 2060.42
  5207.3 2060.33  5221.3 2063.68  5229.5 2064.25  5246.9 2069.05  5252.8 2071.76
#Mann=6,-1,0
  4688.8   0.035       0  5005.7   0.035       0  5009.7   0.035       0
  5028.8    0.16       0  5158.6   0.035       0  5246.9    0.07       0
Bank Sta=5005.7,5009.7
Exp/Cntr=0.3,0.1

Type RM Length L Ch R = 1,283,73,73,73
BEGIN DESCRIPTION:
Elm 68 4492
END DESCRIPTION:
XS GIS Cut Line= 3
      1527300.37      6769043.03      1527512.70      6769034.33
      1527918.64      6768892.53
#Sta/Elev= 30
  4787.5 2055.98  4792.7 2057.14  4832.2 2055.54  4842.2 2054.65  4872.2 2049.27
  4922.2 2046.37  4942.3 2041.39  4962.3 2037.52  4972.3 2036.72  5002.0 2037.05
  5013.0 2034.31  5031.6 2034.23  5036.9 2033.04  5062.7 2033.48  5068.0 2032.25
  5093.7 2032.87  5099.0 2031.44  5119.0 2031.21  5122.8 2028.97  5123.0 2028.47
  5126.8 2028.97  5218.0 2033.94  5267.3 2037.91  5280.1 2040.21  5305.8 2047.56
  5311.1 2047.77  5330.8 2052.95  5336.9 2055.73  5367.9 2057.49  5430.0 2057.79
#Mann=3,-1,0
  4787.5   0.035       0  5122.8   0.035       0  5126.8   0.035       0
Bank Sta=5122.8,5126.8
Exp/Cntr=0.3,0.1