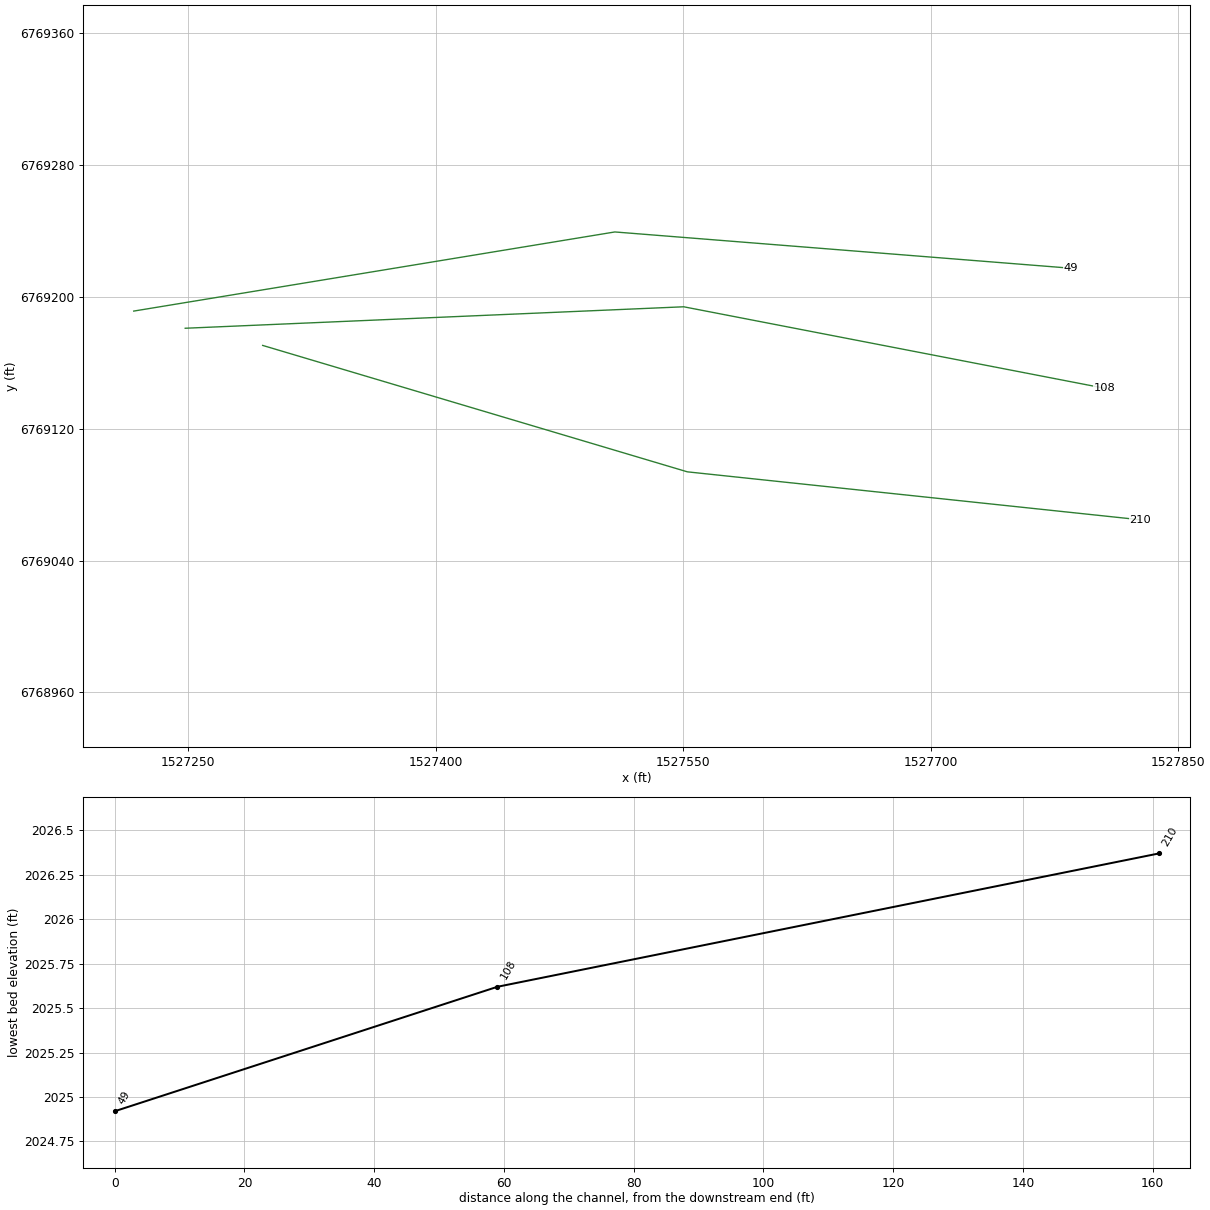
HEC-RAS study Elm 68.prj: Elm 68 Base Level Engineering

--- Elm 68.g01 (geometry) --- (continued)

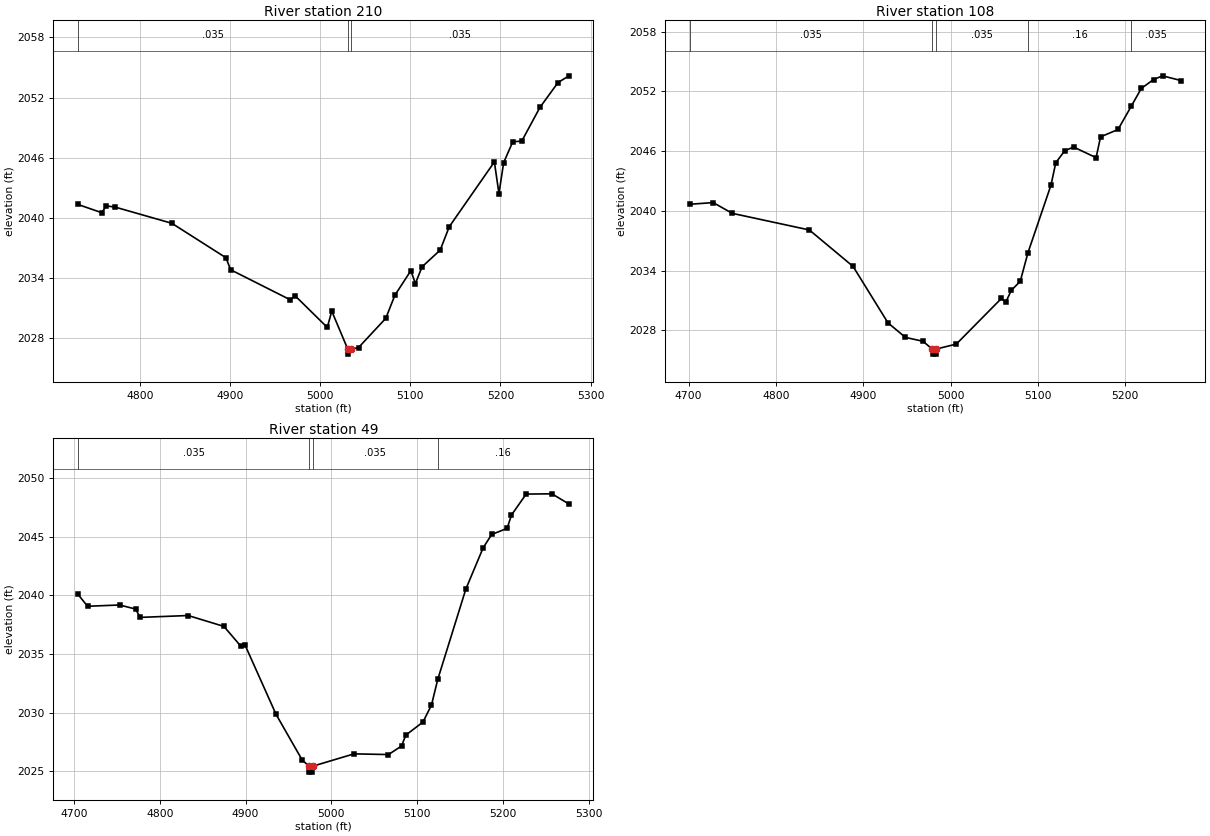
Type RM Length L Ch R = 1,210,102,102,102
BEGIN DESCRIPTION:
Elm 68 4489
END DESCRIPTION:
XS GIS Cut Line= 3
      1527295.22      6769170.63      1527552.62      6769093.88
      1527826.99      6769064.79
#Sta/Elev= 30
  4731.4 2041.32  4757.7 2040.50  4762.9 2041.18  4772.9 2041.05  4835.5 2039.44
  4895.5 2036.00  4900.7 2034.80  4967.0 2031.79  4972.2 2032.20  5007.9 2029.04
  5012.9 2030.66  5030.6 2026.87  5030.8 2026.37  5034.6 2026.87  5042.6 2027.03
  5072.8 2029.95  5082.8 2032.24  5100.6 2034.71  5105.6 2033.42  5113.0 2035.09
  5133.1 2036.76  5143.2 2039.10  5193.2 2045.57  5198.3 2042.41  5203.5 2045.50
  5213.6 2047.58  5223.6 2047.65  5243.7 2051.01  5263.8 2053.50  5275.9 2054.17
#Mann=3,-1,0
  4731.4   0.035       0  5030.6   0.035       0  5034.6   0.035       0
Bank Sta=5030.6,5034.6
Exp/Cntr=0.3,0.1

Type RM Length L Ch R = 1,108,59,59,59
BEGIN DESCRIPTION:
Elm 68 4491
END DESCRIPTION:
XS GIS Cut Line= 3
      1527248.28      6769181.05      1527550.40      6769194.08
      1527805.65      6769144.59
#Sta/Elev= 30
  4701.4 2040.67  4728.1 2040.84  4749.9 2039.76  4838.2 2038.09  4888.3 2034.43
  4928.3 2028.76  4948.3 2027.30  4968.4 2026.91  4979.1 2026.12  4979.3 2025.62
  4982.8 2025.62  4983.1 2026.12  5006.6 2026.63  5058.2 2031.21  5063.2 2030.83
  5069.6 2032.03  5079.8 2032.93  5088.7 2035.82  5115.0 2042.59  5120.5 2044.84
  5130.7 2046.04  5140.9 2046.42  5166.7 2045.35  5171.8 2047.44  5191.8 2048.18
  5207.2 2050.55  5218.5 2052.31  5232.6 2053.20  5242.8 2053.57  5263.8 2053.10
#Mann=5,-1,0
  4701.4   0.035       0  4979.1   0.035       0  4983.1   0.035       0
  5088.7    0.16       0  5207.2   0.035       0
Bank Sta=4979.1,4983.1
Exp/Cntr=0.3,0.1

Type RM Length L Ch R = 1,49,0,0,0
BEGIN DESCRIPTION:
Elm 68 4490
END DESCRIPTION:
XS GIS Cut Line= 3
      1527217.08      6769191.47      1527508.65      6769239.51
      1527784.78      6769217.51
#Sta/Elev= 30
  4704.5 2040.10  4715.7 2039.08  4753.1 2039.19  4771.8 2038.84  4776.9 2038.13
  4833.0 2038.29  4874.7 2037.36  4894.2 2035.69  4899.2 2035.79  4935.5 2029.85
  4965.9 2025.96  4974.0 2025.42  4974.3 2024.92  4977.8 2024.92  4978.0 2025.42
  5026.4 2026.48  5066.6 2026.42  5081.8 2027.15  5086.8 2028.08  5106.7 2029.19
  5116.7 2030.64  5124.0 2032.83  5156.8 2040.55  5176.9 2044.06  5186.9 2045.21
  5204.9 2045.73  5210.0 2046.87  5227.1 2048.66  5257.2 2048.68  5277.0 2047.81
#Mann=4,-1,0
  4704.5   0.035       0  4974.0   0.035       0  4978.0   0.035       0
  5124.0    0.16       0
Bank Sta=4974,4978
Exp/Cntr=0.3,0.1

Chan Stop Cuts=-1