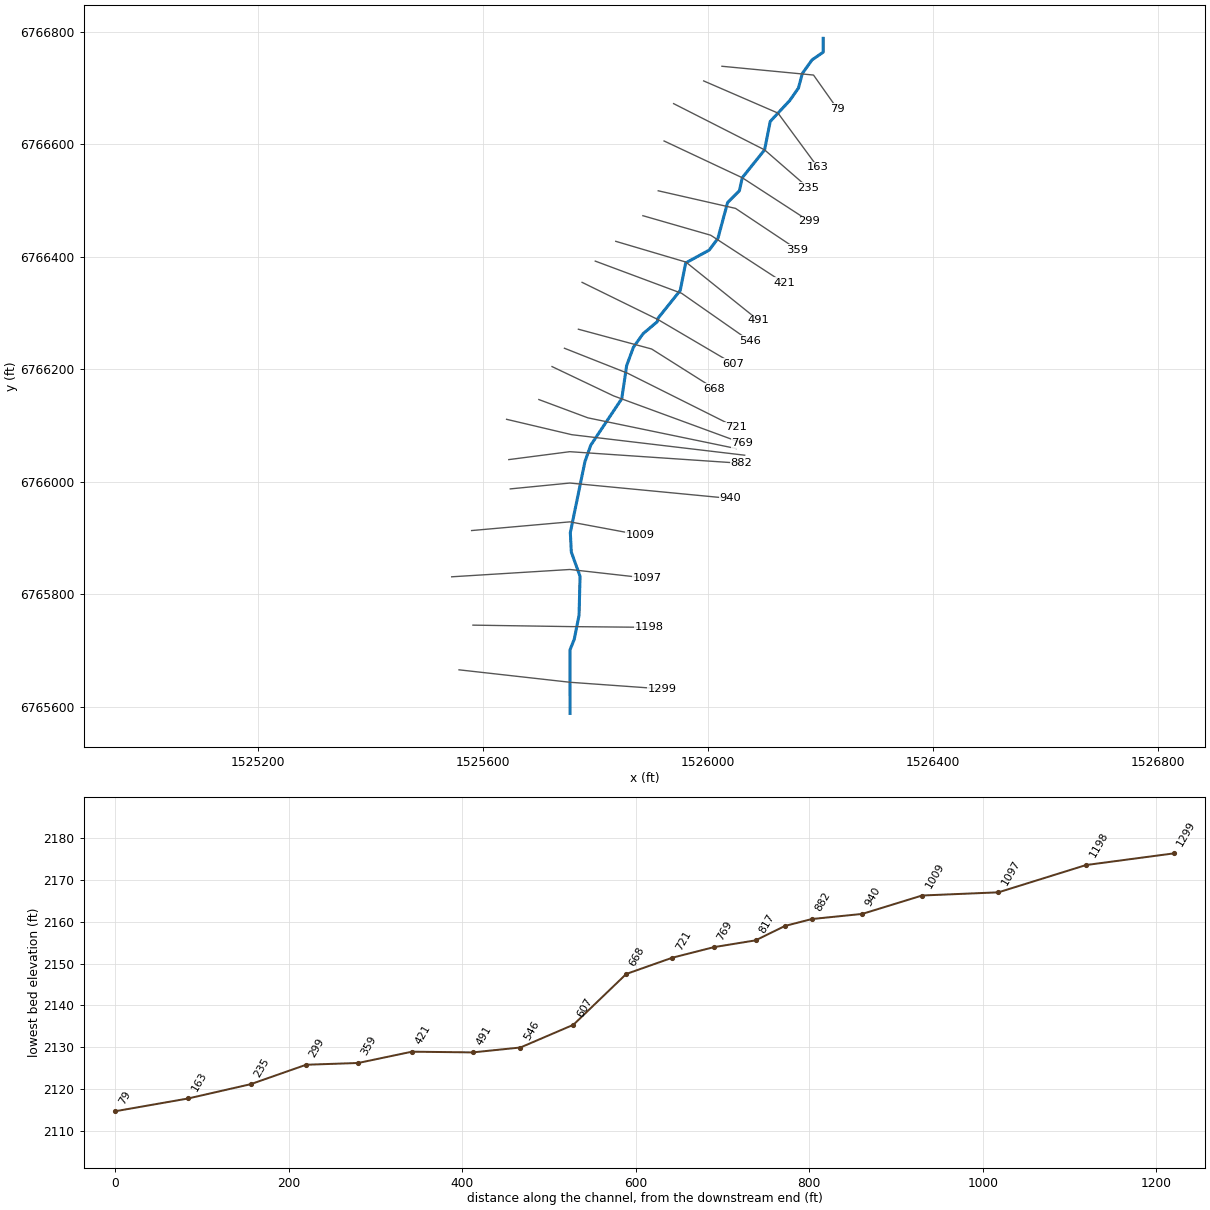
--- Elm 69.prj (project) ---

Proj Title=Elm 69 Base Level Engineering
Current Plan=p01
Default Exp/Contr=0.3,0.1
English Units
Geom File=g01
Flow File=f01
Plan File=p01
BEGIN DESCRIPTION:
Elm 69
END DESCRIPTION:

--- Elm 69.p01 (plan) ---

Plan Title=Multiple Run
Short Identifier=Multiple
Geom File=g01
Flow File=f01
Subcritical Flow
K Sum by GR= 0
Std Step Tol= 0.01
Critical Tol= 0.01
Num of Std Step Trials= 20
Max Error Tol= 0.3
Flow Tol Ratio= 0.001
Split Flow NTrial= 30
Split Flow Tol= 0.02
Split Flow Ratio= 0.02
Log Output Level= 0
Friction Slope Method= 1
Unsteady Friction Slope Method= 2
Unsteady Bridges Friction Slope Method= 1
Parabolic Critical Depth
Global Vel Dist=  1 , 1 , 1
Global Log Level= 0
CheckData=True
Encroach Param= -1, 0, 0, 0
BEGIN DESCRIPTION:
Multiple Run
END DESCRIPTION:

--- Elm 69.f01 (steady flow) ---

Flow Title=Multiple
Number of Profiles=7
Profile Names=10-year,25-year,50-year,1pct_min,100-year,1pct_plu,500-year
River Rch & RM= Elm 69,Reach-1,1299
      52      66      77      56      89     123     123
Boundary for River Rch & Prof#=Elm 69,Reach-1,1
Up Type=0
Dn Type=3
Dn Slope=0.005
Boundary for River Rch & Prof#=Elm 69,Reach-1,2
Up Type=0
Dn Type=3
Dn Slope=0.005
Boundary for River Rch & Prof#=Elm 69,Reach-1,3
Up Type=0
Dn Type=3
Dn Slope=0.005
Boundary for River Rch & Prof#=Elm 69,Reach-1,4
Up Type=0
Dn Type=3
Dn Slope=0.005
Boundary for River Rch & Prof#=Elm 69,Reach-1,5
Up Type=0
Dn Type=3
Dn Slope=0.005
Boundary for River Rch & Prof#=Elm 69,Reach-1,6
Up Type=0
Dn Type=3
Dn Slope=0.005
Boundary for River Rch & Prof#=Elm 69,Reach-1,7
Up Type=0
Dn Type=3
Dn Slope=0.005

--- Elm 69.g01 (geometry) ---

Geom Title=Existing Conditions

River Reach=Elm 69,Reach-1
Reach XY= 30
      1525755.00      6765588.00      1525754.88      6765700.79
      1525762.38      6765719.53      1525771.00      6765762.67
      1525772.73      6765831.69      1525757.20      6765874.82
      1525755.47      6765909.33      1525781.36      6766035.29
      1525791.71      6766064.63      1525846.93      6766147.45
      1525855.55      6766206.12      1525867.63      6766238.90
      1525884.89      6766263.06      1525909.99      6766284.21
      1525911.10      6766290.19      1525950.81      6766339.73
      1525960.54      6766388.74      1526002.22      6766411.45
      1526017.75      6766432.16      1526035.00      6766496.00
      1526056.02      6766517.02      1526061.10      6766540.19
      1526100.81      6766589.73      1526110.84      6766640.30
      1526145.50      6766677.44      1526160.96      6766699.61
      1526167.87      6766725.49      1526185.12      6766749.65
      1526205.05      6766763.45      1526205.00      6766788.00

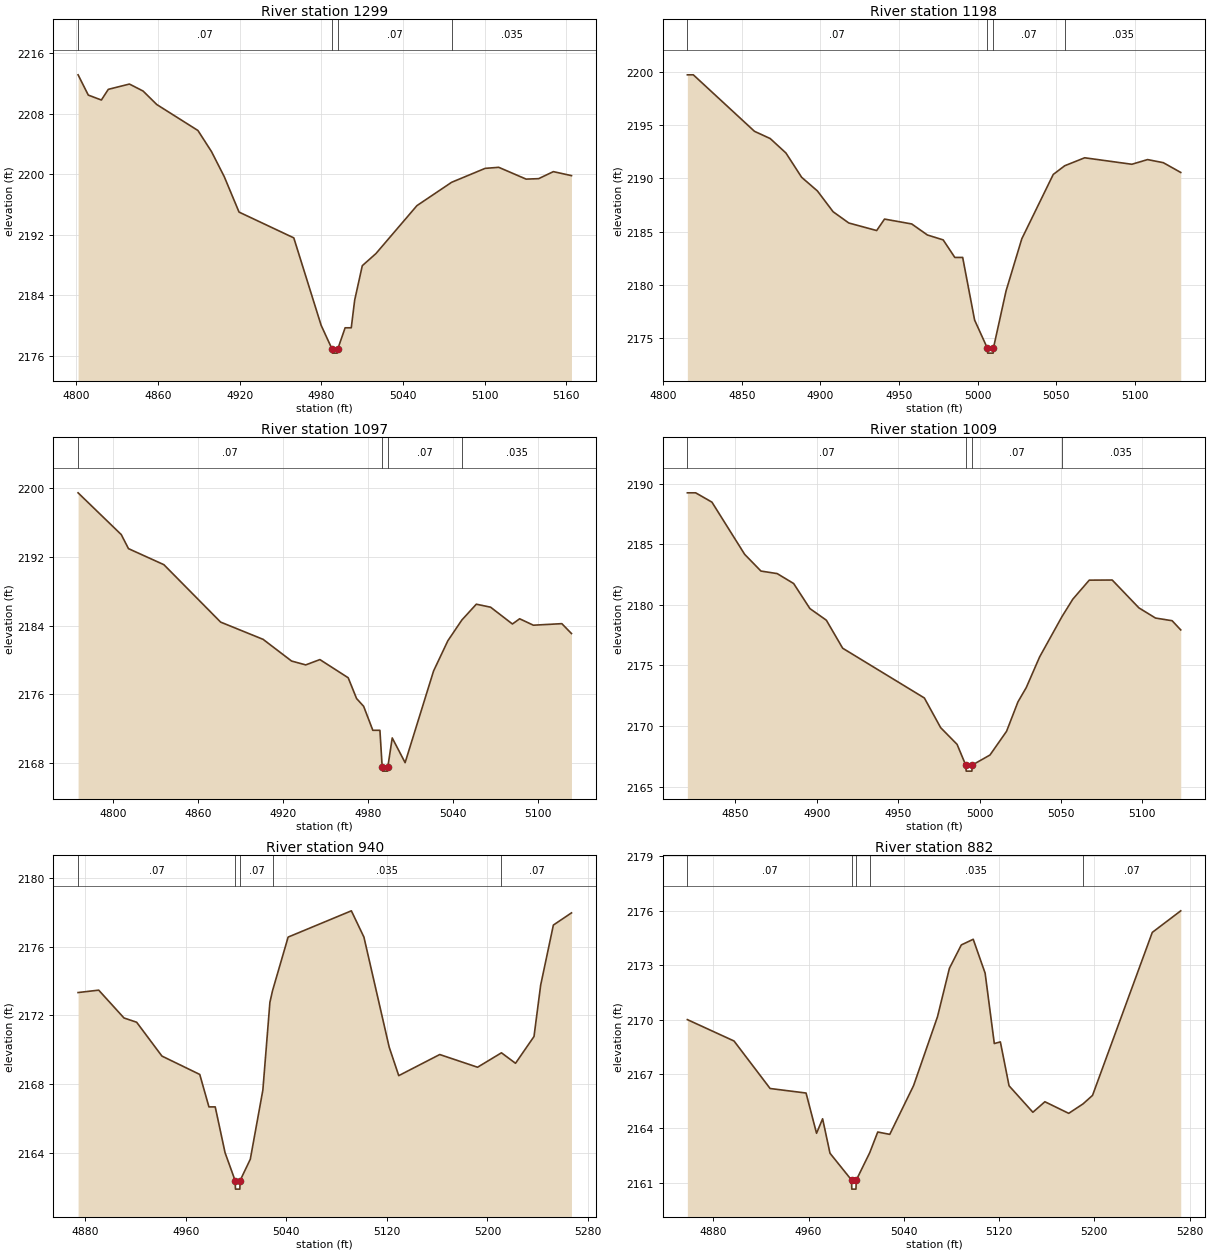
Type RM Length L Ch R = 1,1299,101,101,101
BEGIN DESCRIPTION:
Elm 69 4595
END DESCRIPTION:
XS GIS Cut Line= 3
      1525557.58      6765665.43      1525754.94      6765643.29
      1525918.22      6765631.58
#Sta/Elev= 30
  4801.4 2213.13  4808.9 2210.45  4818.5 2209.80  4823.6 2211.21  4839.1 2211.91
  4849.1 2210.99  4859.2 2209.20  4889.4 2205.77  4899.4 2202.97  4908.7 2199.68
  4919.6 2194.98  4959.8 2191.57  4979.9 2180.00  4988.0 2176.83  4988.2 2176.33
  4991.7 2176.33  4992.0 2176.83  4997.5 2179.68  5002.0 2179.68  5004.5 2183.33
  5010.1 2187.89  5020.1 2189.49  5050.2 2195.83  5075.7 2198.92  5100.3 2200.76
  5110.3 2200.90  5130.4 2199.34  5139.6 2199.40  5150.4 2200.33  5163.7 2199.80
#Mann=4,-1,0
  4801.4    0.07       0  4988.0    0.07       0  4992.0    0.07       0
  5075.7   0.035       0
Bank Sta=4988,4992
Exp/Cntr=0.3,0.1

Type RM Length L Ch R = 1,1198,101,101,101
BEGIN DESCRIPTION:
Elm 69 4596
END DESCRIPTION:
XS GIS Cut Line= 3
      1525582.32      6765744.86      1525754.84      6765742.26
      1525896.09      6765740.95
#Sta/Elev= 30
  4815.4 2199.75  4819.2 2199.75  4858.1 2194.43  4868.1 2193.75  4878.1 2192.39
  4888.1 2190.10  4898.1 2188.82  4908.1 2186.86  4918.1 2185.80  4935.8 2185.09
  4940.8 2186.17  4958.1 2185.71  4968.1 2184.67  4978.1 2184.21  4985.5 2182.56
  4990.5 2182.56  4998.1 2176.66  5006.1 2174.05  5006.4 2173.55  5009.9 2173.55
  5010.1 2174.05  5018.1 2179.41  5028.1 2184.31  5048.1 2190.37  5055.4 2191.19
  5068.1 2191.94  5098.1 2191.33  5108.1 2191.77  5118.1 2191.48  5129.2 2190.56
#Mann=4,-1,0
  4815.4    0.07       0  5006.1    0.07       0  5010.1    0.07       0
  5055.4   0.035       0
Bank Sta=5006.1,5010.1
Exp/Cntr=0.3,0.1

Type RM Length L Ch R = 1,1097,88,88,88
BEGIN DESCRIPTION:
Elm 69 4597
END DESCRIPTION:
XS GIS Cut Line= 3
      1525544.53      6765830.79      1525754.73      6765843.80
      1525891.77      6765828.38
#Sta/Elev= 30
  4775.1 2199.49  4805.6 2194.62  4810.7 2192.98  4835.7 2191.11  4875.8 2184.41
  4905.8 2182.40  4925.9 2179.87  4935.9 2179.42  4945.9 2180.04  4965.9 2177.92
  4971.8 2175.50  4976.8 2174.59  4983.3 2171.79  4988.3 2171.79  4989.9 2167.53
  4990.2 2167.03  4993.7 2167.03  4993.9 2167.53  4997.0 2170.90  5006.1 2168.02
  5026.2 2178.71  5036.3 2182.24  5046.2 2184.66  5056.4 2186.50  5066.5 2186.15
  5081.9 2184.19  5087.0 2184.80  5096.7 2184.05  5116.8 2184.23  5123.6 2183.08
#Mann=4,-1,0
  4775.1    0.07       0  4989.9    0.07       0  4993.9    0.07       0
  5046.2   0.035       0
Bank Sta=4989.9,4993.9
Exp/Cntr=0.3,0.1

Type RM Length L Ch R = 1,1009,69,69,69
BEGIN DESCRIPTION:
Elm 69 4598
END DESCRIPTION:
XS GIS Cut Line= 3
      1525579.97      6765913.00      1525754.64      6765928.46
      1525880.22      6765905.06
#Sta/Elev= 30
  4820.5 2189.25  4825.6 2189.25  4835.6 2188.48  4855.7 2184.17  4865.7 2182.79
  4875.7 2182.58  4885.8 2181.76  4895.8 2179.69  4905.9 2178.73  4915.9 2176.42
  4966.1 2172.31  4976.1 2169.86  4986.2 2168.48  4991.5 2166.77  4991.8 2166.27
  4995.3 2166.27  4995.5 2166.77  5006.4 2167.60  5016.6 2169.56  5023.6 2171.99
  5028.7 2173.17  5036.9 2175.70  5050.6 2179.02  5057.3 2180.47  5067.4 2182.04
  5081.5 2182.05  5097.9 2179.75  5108.1 2178.91  5118.3 2178.69  5123.6 2177.93
#Mann=4,-1,0
  4820.5    0.07       0  4991.5    0.07       0  4995.5    0.07       0
  5050.6   0.035       0
Bank Sta=4991.5,4995.5
Exp/Cntr=0.3,0.1

Type RM Length L Ch R = 1,940,58,58,58
BEGIN DESCRIPTION:
Elm 69 4594
END DESCRIPTION:
XS GIS Cut Line= 3
      1525648.67      6765987.04      1525754.57      6765997.46
      1526039.35      6765970.12
#Sta/Elev= 30
  4874.3 2173.32  4890.7 2173.46  4910.8 2171.84  4920.9 2171.59  4941.0 2169.62
  4971.1 2168.55  4978.4 2166.66  4983.4 2166.66  4991.2 2164.00  4999.2 2162.37
  4999.5 2161.87  5003.0 2161.87  5003.2 2162.37  5011.3 2163.61  5021.3 2167.64
  5026.9 2172.75  5029.0 2173.43  5041.4 2176.55  5091.7 2178.08  5101.7 2176.55
  5121.8 2170.14  5129.4 2168.48  5162.0 2169.71  5192.1 2168.97  5211.1 2169.81
  5222.3 2169.20  5237.0 2170.76  5242.3 2173.75  5252.4 2177.25  5266.8 2177.96
#Mann=5,-1,0
  4874.3    0.07       0  4999.2    0.07       0  5003.2    0.07       0
  5029.0   0.035       0  5211.1    0.07       0
Bank Sta=4999.2,5003.2
Exp/Cntr=0.3,0.1

Type RM Length L Ch R = 1,882,31,31,31
BEGIN DESCRIPTION:
Elm 69 894.059
END DESCRIPTION:
XS GIS Cut Line= 3
      1525646.09      6766039.13      1525754.51      6766053.20
      1526058.88      6766032.62
#Sta/Elev= 30
  4858.2 2170.00  4897.4 2168.82  4927.7 2166.20  4957.9 2165.95  4966.7 2163.73
  4971.8 2164.53  4978.0 2162.63  4996.1 2161.15  4996.3 2160.65  4999.8 2160.65
  5000.1 2161.15  5011.3 2162.65  5018.1 2163.80  5028.2 2163.67  5048.2 2166.36
  5068.3 2170.16  5078.3 2172.83  5088.3 2174.12  5098.3 2174.43  5108.3 2172.56
  5116.0 2168.68  5121.1 2168.77  5128.4 2166.35  5148.4 2164.89  5158.5 2165.47
  5178.5 2164.83  5190.5 2165.35  5198.5 2165.82  5248.7 2174.81  5272.6 2176.00
#Mann=5,-1,0
  4858.2    0.07       0  4996.1    0.07       0  5000.1    0.07       0
  5011.3   0.035       0  5190.5    0.07       0
Bank Sta=4996.1,5000.1
Exp/Cntr=0.3,0.1

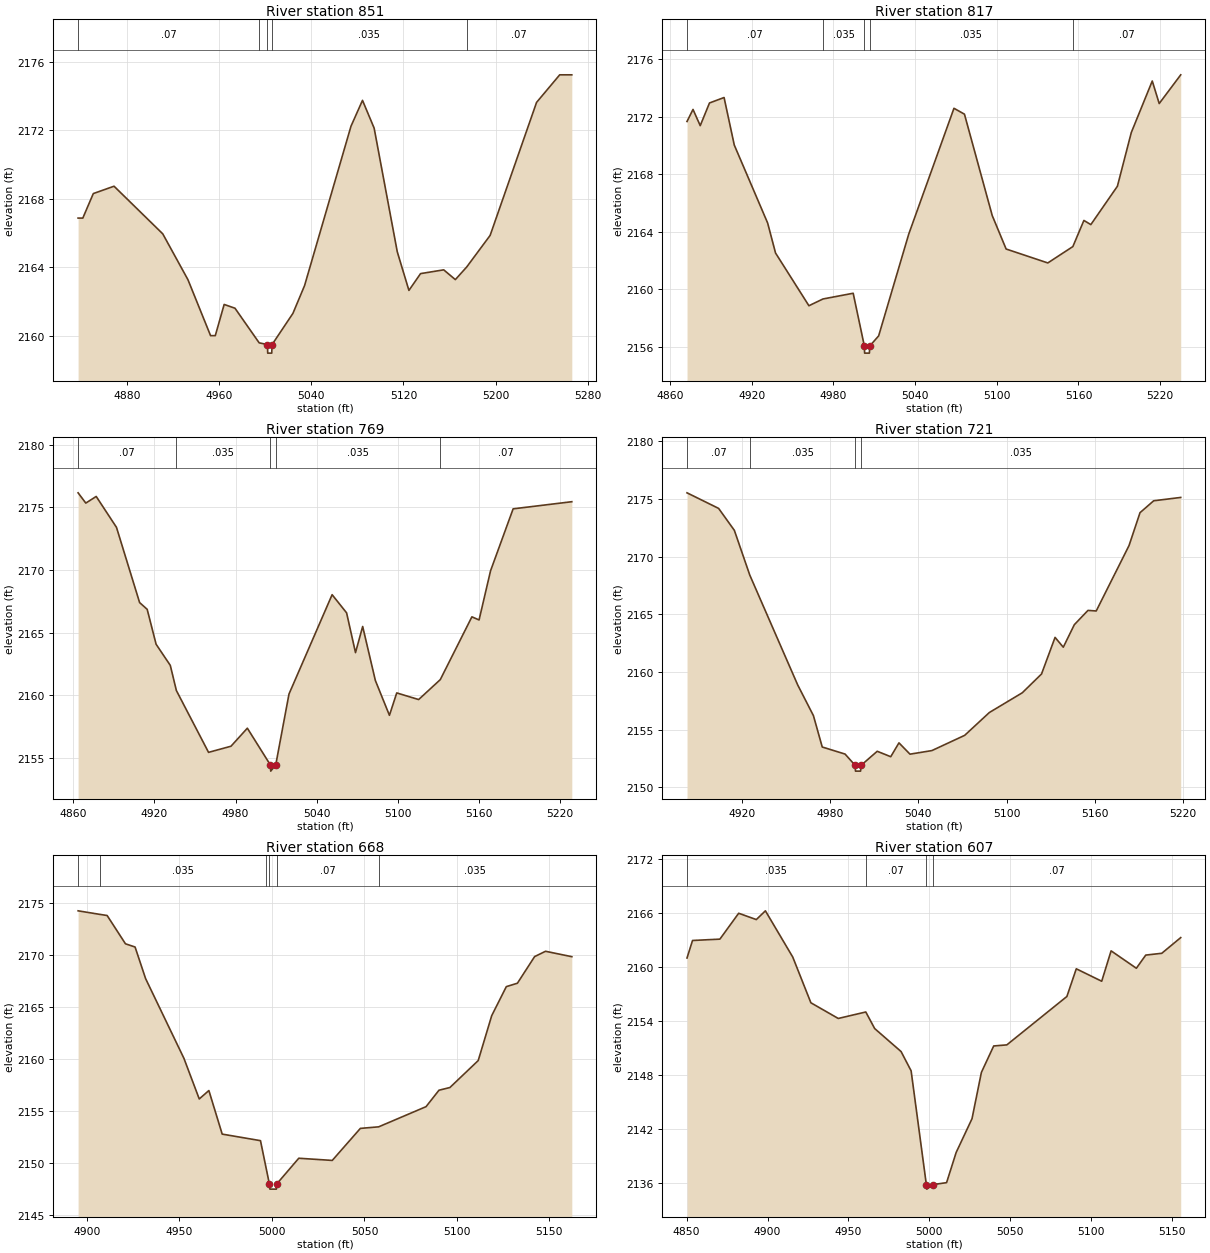
Type RM Length L Ch R = 1,851,34,34,34
BEGIN DESCRIPTION:
Elm 69 863.65
END DESCRIPTION:
XS GIS Cut Line= 3
      1525642.15      6766110.75      1525758.08      6766083.40
      1526065.41      6766046.94
#Sta/Elev= 30
  4837.6 2166.88  4841.7 2166.88  4850.8 2168.31  4868.8 2168.74  4911.1 2165.96
  4933.0 2163.28  4952.6 2160.02  4956.7 2160.02  4964.4 2161.84  4973.8 2161.62
  4994.8 2159.60  5002.0 2159.50  5002.2 2159.00  5005.7 2159.00  5006.0 2159.50
  5024.1 2161.32  5034.2 2162.94  5074.5 2172.24  5084.5 2173.75  5094.6 2172.13
  5114.7 2164.91  5124.8 2162.66  5134.9 2163.64  5155.0 2163.86  5165.1 2163.29
  5175.0 2164.03  5195.3 2165.87  5235.6 2173.63  5255.7 2175.24  5266.2 2175.24
#Mann=5,-1,0
  4837.6    0.07       0  4994.8   0.035       0  5002.0   0.035       0
  5006.0   0.035       0  5175.0    0.07       0
Bank Sta=5002,5006
Exp/Cntr=0.3,0.1

Type RM Length L Ch R = 1,817,48,48,48
BEGIN DESCRIPTION:
Elm 69 823.57
END DESCRIPTION:
XS GIS Cut Line= 3
      1525699.50      6766145.89      1525786.73      6766113.35
      1526050.54      6766058.76
#Sta/Elev= 30
  4872.6 2171.68  4877.0 2172.52  4882.3 2171.39  4889.1 2172.97  4899.8 2173.35
  4907.3 2170.04  4931.8 2164.61  4937.6 2162.52  4962.1 2158.85  4972.4 2159.32
  4994.6 2159.72  5002.8 2156.05  5003.0 2155.55  5006.5 2155.55  5006.8 2156.05
  5013.3 2156.75  5035.4 2163.84  5068.6 2172.60  5076.3 2172.19  5096.7 2165.13
  5106.9 2162.80  5137.5 2161.83  5155.9 2162.97  5164.0 2164.79  5169.1 2164.50
  5188.6 2167.17  5198.8 2170.91  5214.2 2174.50  5219.3 2172.93  5235.1 2174.93
#Mann=5,-1,0
  4872.6    0.07       0  4972.4   0.035       0  5002.8   0.035       0
  5006.8   0.035       0  5155.9    0.07       0
Bank Sta=5002.8,5006.8
Exp/Cntr=0.3,0.1

Type RM Length L Ch R = 1,769,48,48,48
BEGIN DESCRIPTION:
Elm 69 764.98
END DESCRIPTION:
XS GIS Cut Line= 3
      1525722.93      6766204.49      1525832.30      6766152.41
      1526061.40      6766068.28
#Sta/Elev= 30
  4863.5 2176.17  4869.2 2175.35  4876.9 2175.88  4891.9 2173.41  4909.0 2167.40
  4914.6 2166.86  4921.2 2164.07  4931.7 2162.38  4936.2 2160.37  4960.0 2155.43
  4976.6 2155.92  4988.7 2157.36  5005.7 2154.43  5006.0 2153.93  5009.7 2154.43
  5019.5 2160.09  5051.4 2168.03  5062.1 2166.58  5068.7 2163.40  5074.0 2165.49
  5083.4 2161.17  5093.8 2158.39  5099.2 2160.18  5115.4 2159.65  5131.4 2161.24
  5154.8 2166.26  5160.1 2166.01  5168.6 2169.94  5185.3 2174.89  5228.7 2175.46
#Mann=5,-1,0
  4863.5    0.07       0  4936.2   0.035       0  5005.7   0.035       0
  5009.7   0.035       0  5131.4    0.07       0
Bank Sta=5005.7,5009.7
Exp/Cntr=0.3,0.1

Type RM Length L Ch R = 1,721,53,53,53
BEGIN DESCRIPTION:
Elm 69 715.15
END DESCRIPTION:
XS GIS Cut Line= 3
      1525745.02      6766237.06      1525857.04      6766192.77
      1526049.74      6766096.43
#Sta/Elev= 30
  4882.6 2175.52  4904.1 2174.17  4914.8 2172.27  4925.3 2168.39  4957.9 2158.87
  4968.6 2156.21  4974.6 2153.49  4990.1 2152.88  4997.0 2151.90  4997.2 2151.40
  5000.7 2151.40  5001.0 2151.90  5012.0 2153.12  5021.2 2152.65  5026.8 2153.85
  5034.3 2152.87  5049.2 2153.18  5071.5 2154.50  5088.3 2156.48  5110.7 2158.19
  5123.8 2159.82  5133.0 2162.99  5138.6 2162.14  5146.1 2164.09  5155.4 2165.33
  5161.0 2165.28  5183.3 2170.94  5190.8 2173.80  5200.1 2174.83  5218.5 2175.12
#Mann=4,-1,0
  4882.6    0.07       0  4925.3   0.035       0  4997.0   0.035       0
  5001.0   0.035       0
Bank Sta=4997,5001
Exp/Cntr=0.3,0.1

Type RM Length L Ch R = 1,668,61,61,61
BEGIN DESCRIPTION:
Elm 69 655.01
END DESCRIPTION:
XS GIS Cut Line= 3
      1525769.80      6766270.90      1525900.01      6766235.74
      1526011.60      6766165.19
#Sta/Elev= 30
  4895.2 2174.28  4906.9 2173.94  4910.9 2173.83  4920.8 2171.11  4926.0 2170.80
  4931.7 2167.76  4952.4 2160.10  4960.7 2156.19  4965.9 2157.00  4973.1 2152.81
  4993.8 2152.18  4997.0 2149.41  4998.6 2148.02  4998.9 2147.52  5002.4 2147.52
  5002.6 2148.02  5014.5 2150.49  5032.6 2150.28  5047.8 2153.36  5057.7 2153.51
  5083.3 2155.45  5090.3 2157.03  5096.2 2157.29  5111.5 2159.88  5118.8 2164.20
  5126.7 2166.99  5132.7 2167.32  5142.0 2169.88  5147.9 2170.39  5162.1 2169.87
#Mann=6,-1,0
  4895.2    0.07       0  4906.9   0.035       0  4997.0    0.07       0
  4998.6    0.07       0  5002.6    0.07       0  5057.7   0.035       0
Bank Sta=4998.6,5002.6
Exp/Cntr=0.3,0.1

Type RM Length L Ch R = 1,607,61,61,61
BEGIN DESCRIPTION:
Elm 69 601.19
END DESCRIPTION:
XS GIS Cut Line= 3
      1525776.34      6766354.22      1525911.73      6766287.83
      1526044.56      6766209.69
#Sta/Elev= 30
  4850.3 2161.01  4853.7 2162.95  4870.6 2163.10  4882.2 2165.97  4893.1 2165.27
  4898.7 2166.24  4915.6 2161.11  4926.8 2156.04  4943.7 2154.30  4960.7 2155.02
  4966.2 2153.18  4982.5 2150.63  4988.7 2148.49  4998.1 2135.87  4998.4 2135.37
  5002.1 2135.87  5010.6 2136.09  5016.5 2139.43  5026.3 2143.18  5032.1 2148.32
  5039.7 2151.25  5047.8 2151.37  5084.9 2156.74  5090.7 2159.81  5106.4 2158.43
  5112.2 2161.80  5127.8 2159.87  5133.6 2161.33  5143.5 2161.53  5155.2 2163.27
#Mann=4,-1,0
  4850.3   0.035       0  4960.7    0.07       0  4998.1    0.07       0
  5002.1    0.07       0
Bank Sta=4998.1,5002.1
Exp/Cntr=0.3,0.1

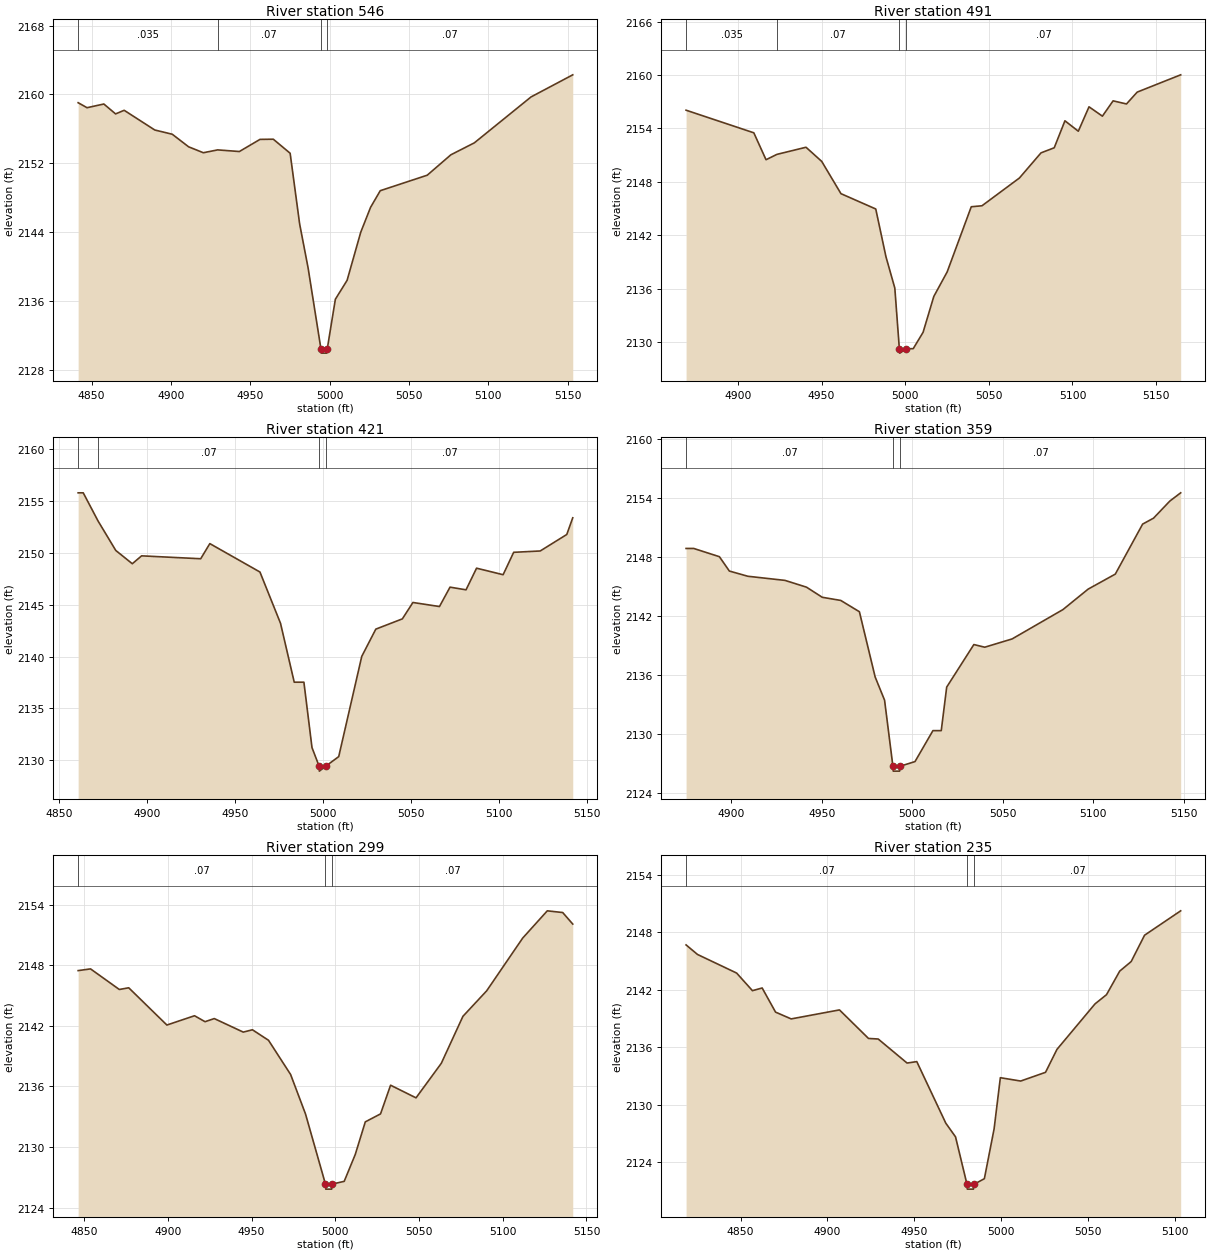
Type RM Length L Ch R = 1,546,55,55,55
BEGIN DESCRIPTION:
Elm 69 539.8
END DESCRIPTION:
XS GIS Cut Line= 3
      1525799.79      6766391.98      1525953.39      6766334.70
      1526074.51      6766250.05
#Sta/Elev= 30
  4841.5 2159.04  4847.1 2158.46  4857.7 2158.89  4865.1 2157.74  4870.5 2158.16
  4889.8 2155.87  4900.8 2155.38  4911.1 2153.92  4920.4 2153.23  4929.4 2153.56
  4943.1 2153.37  4956.1 2154.78  4964.5 2154.80  4975.1 2153.17  4981.1 2144.94
  4986.4 2139.87  4994.5 2130.45  4994.7 2129.95  4998.2 2129.95  4998.5 2130.45
  5003.6 2136.21  5011.0 2138.41  5019.6 2144.00  5025.8 2146.89  5031.9 2148.82
  5061.5 2150.62  5076.4 2152.99  5091.2 2154.38  5126.9 2159.71  5153.2 2162.28
#Mann=4,-1,0
  4841.5   0.035       0  4929.4    0.07       0  4994.5    0.07       0
  4998.5    0.07       0
Bank Sta=4994.5,4998.5
Exp/Cntr=0.3,0.1

Type RM Length L Ch R = 1,491,70,70,70
BEGIN DESCRIPTION:
Elm 69 484.236
END DESCRIPTION:
XS GIS Cut Line= 3
      1525836.21      6766427.15      1525960.85      6766390.29
      1526090.08      6766286.55
#Sta/Elev= 30
  4869.0 2156.05  4909.5 2153.51  4916.8 2150.49  4923.3 2151.09  4940.7 2151.89
  4950.1 2150.30  4961.6 2146.68  4982.4 2144.96  4988.5 2139.60  4993.8 2136.08
  4996.5 2129.28  4996.8 2128.78  5000.5 2129.28  5004.8 2129.28  5010.7 2131.12
  5017.1 2135.14  5025.1 2137.90  5039.5 2145.21  5045.9 2145.32  5068.3 2148.44
  5081.2 2151.26  5089.1 2151.83  5095.5 2154.86  5103.5 2153.69  5109.9 2156.43
  5117.9 2155.38  5124.3 2157.10  5132.3 2156.75  5138.7 2158.08  5164.7 2160.02
#Mann=4,-1,0
  4869.0   0.035       0  4923.3    0.07       0  4996.5    0.07       0
  5000.5    0.07       0
Bank Sta=4996.5,5000.5
Exp/Cntr=0.3,0.1

Type RM Length L Ch R = 1,421,62,62,62
BEGIN DESCRIPTION:
Elm 69 4582
END DESCRIPTION:
XS GIS Cut Line= 3
      1525884.43      6766472.71      1526005.00      6766438.00
      1526135.60      6766352.98
#Sta/Elev= 30
  4860.8 2155.80  4863.7 2155.80  4872.1 2153.09  4882.2 2150.24  4891.6 2148.96
  4896.9 2149.72  4930.5 2149.44  4935.7 2150.90  4964.2 2148.16  4975.9 2143.21
  4983.7 2137.53  4989.2 2137.53  4993.8 2131.22  4997.8 2129.45  4998.0 2128.95
  5001.8 2129.45  5009.0 2130.35  5022.1 2140.02  5030.1 2142.65  5045.2 2143.64
  5051.2 2145.22  5066.3 2144.83  5072.3 2146.70  5081.4 2146.44  5087.4 2148.53
  5102.5 2147.90  5108.5 2150.06  5123.6 2150.19  5138.7 2151.78  5142.1 2153.39
#Mann=4,-1,0
  4860.8   0.035       0  4872.1    0.07       0  4997.8    0.07       0
  5001.8    0.07       0
Bank Sta=4997.8,5001.8
Exp/Cntr=0.3,0.1

Type RM Length L Ch R = 1,359,60,60,60
BEGIN DESCRIPTION:
Elm 69 4581
END DESCRIPTION:
XS GIS Cut Line= 3
      1525911.72      6766516.99      1526049.15      6766485.71
      1526159.11      6766412.40
#Sta/Elev= 30
  4875.1 2148.91  4879.3 2148.91  4893.5 2148.07  4899.0 2146.61  4909.2 2146.08
  4929.7 2145.66  4941.6 2144.97  4950.3 2143.94  4960.5 2143.62  4970.8 2142.47
  4979.5 2135.83  4984.7 2133.47  4989.3 2126.75  4989.5 2126.25  4993.0 2126.25
  4993.3 2126.75  5001.5 2127.22  5011.4 2130.37  5016.0 2130.37  5019.0 2134.80
  5034.0 2139.13  5040.0 2138.86  5055.1 2139.70  5083.2 2142.69  5097.1 2144.77
  5112.1 2146.30  5127.2 2151.39  5133.2 2151.99  5142.2 2153.73  5148.2 2154.57
#Mann=3,-1,0
  4875.1    0.07       0  4989.3    0.07       0  4993.3    0.07       0
Bank Sta=4989.3,4993.3
Exp/Cntr=0.3,0.1

Type RM Length L Ch R = 1,299,64,64,64
BEGIN DESCRIPTION:
Elm 69 4580
END DESCRIPTION:
XS GIS Cut Line= 3
      1525922.11      6766605.55      1526061.10      6766540.19
      1526180.04      6766462.98
#Sta/Elev= 30
  4846.4 2147.47  4853.8 2147.64  4871.0 2145.60  4876.6 2145.77  4899.4 2142.08
  4915.9 2143.00  4922.2 2142.41  4927.7 2142.72  4945.0 2141.38  4950.5 2141.61
  4960.1 2140.57  4973.3 2137.18  4982.2 2133.27  4994.1 2126.33  4994.3 2125.83
  4997.8 2125.83  4998.1 2126.33  5005.3 2126.60  5011.9 2129.26  5017.9 2132.49
  5027.0 2133.28  5033.0 2136.12  5048.2 2134.87  5063.3 2138.29  5076.2 2142.94
  5090.4 2145.47  5111.9 2150.69  5126.6 2153.39  5135.8 2153.22  5141.8 2152.08
#Mann=3,-1,0
  4846.4    0.07       0  4994.1    0.07       0  4998.1    0.07       0
Bank Sta=4994.1,4998.1
Exp/Cntr=0.3,0.1

Type RM Length L Ch R = 1,235,72,72,72
BEGIN DESCRIPTION:
Elm 69 4579
END DESCRIPTION:
XS GIS Cut Line= 3
      1525939.10      6766671.92      1526100.81      6766589.73
      1526178.77      6766521.96
#Sta/Elev= 30
  4818.6 2146.69  4825.2 2145.69  4847.7 2143.75  4856.8 2141.91  4862.4 2142.19
  4870.1 2139.67  4879.1 2138.96  4906.9 2139.90  4923.6 2136.92  4929.2 2136.86
  4945.8 2134.35  4951.4 2134.50  4968.1 2128.07  4973.7 2126.64  4980.3 2121.68
  4980.5 2121.18  4984.0 2121.18  4984.3 2121.68  4990.3 2122.27  4995.9 2127.47
  4999.5 2132.82  5011.2 2132.47  5025.5 2133.38  5032.1 2135.78  5054.0 2140.53
  5060.6 2141.49  5068.2 2143.95  5074.8 2144.95  5082.5 2147.70  5103.3 2150.25
#Mann=3,-1,0
  4818.6    0.07       0  4980.3    0.07       0  4984.3    0.07       0
Bank Sta=4980.3,4984.3
Exp/Cntr=0.3,0.1

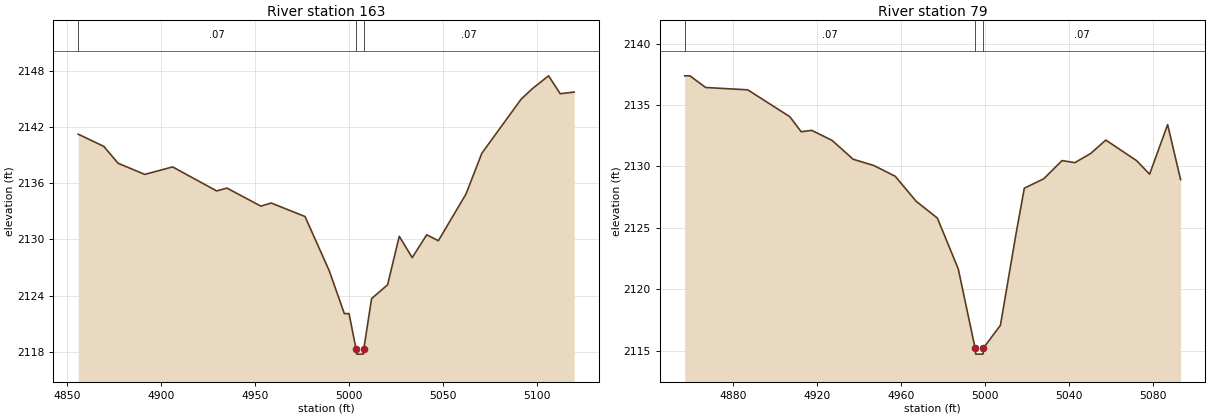
Type RM Length L Ch R = 1,163,84,84,84
BEGIN DESCRIPTION:
Elm 69 4578
END DESCRIPTION:
XS GIS Cut Line= 3
      1525992.49      6766712.29      1526124.63      6766655.08
      1526195.57      6766558.67
#Sta/Elev= 30
  4856.0 2141.22  4869.6 2139.92  4877.2 2138.12  4891.4 2136.93  4906.2 2137.73
  4929.6 2135.17  4935.1 2135.47  4953.1 2133.55  4958.6 2133.88  4976.6 2132.44
  4989.5 2126.65  4997.5 2122.09  5000.0 2122.09  5003.8 2118.27  5004.1 2117.77
  5007.6 2117.77  5007.8 2118.27  5012.0 2123.69  5020.5 2125.16  5026.7 2130.33
  5033.6 2128.06  5041.3 2130.49  5047.5 2129.86  5062.2 2134.84  5070.6 2139.18
  5091.5 2144.95  5097.7 2146.11  5106.1 2147.44  5112.3 2145.53  5119.7 2145.71
#Mann=3,-1,0
  4856.0    0.07       0  5003.8    0.07       0  5007.8    0.07       0
Bank Sta=5003.8,5007.8
Exp/Cntr=0.3,0.1

Type RM Length L Ch R = 1,79,0,0,0
BEGIN DESCRIPTION:
Elm 69 4577
END DESCRIPTION:
XS GIS Cut Line= 3
      1526025.00      6766738.35      1526187.76      6766722.73
      1526230.02      6766662.97
#Sta/Elev= 30
  4856.7 2137.38  4859.2 2137.38  4866.7 2136.43  4886.8 2136.24  4906.9 2134.05
  4912.3 2132.83  4917.3 2132.94  4927.0 2132.13  4937.1 2130.59  4947.1 2130.07
  4957.2 2129.20  4967.2 2127.16  4977.3 2125.80  4987.3 2121.65  4995.3 2115.22
  4995.6 2114.72  4999.1 2114.72  4999.3 2115.22  5007.4 2117.07  5014.9 2124.57
  5018.8 2128.23  5028.1 2129.00  5036.8 2130.48  5042.9 2130.31  5050.5 2131.06
  5057.7 2132.15  5072.5 2130.46  5078.6 2129.37  5087.2 2133.41  5093.4 2128.93
#Mann=3,-1,0
  4856.7    0.07       0  4995.3    0.07       0  4999.3    0.07       0
Bank Sta=4995.3,4999.3
Exp/Cntr=0.3,0.1

Chan Stop Cuts=-1