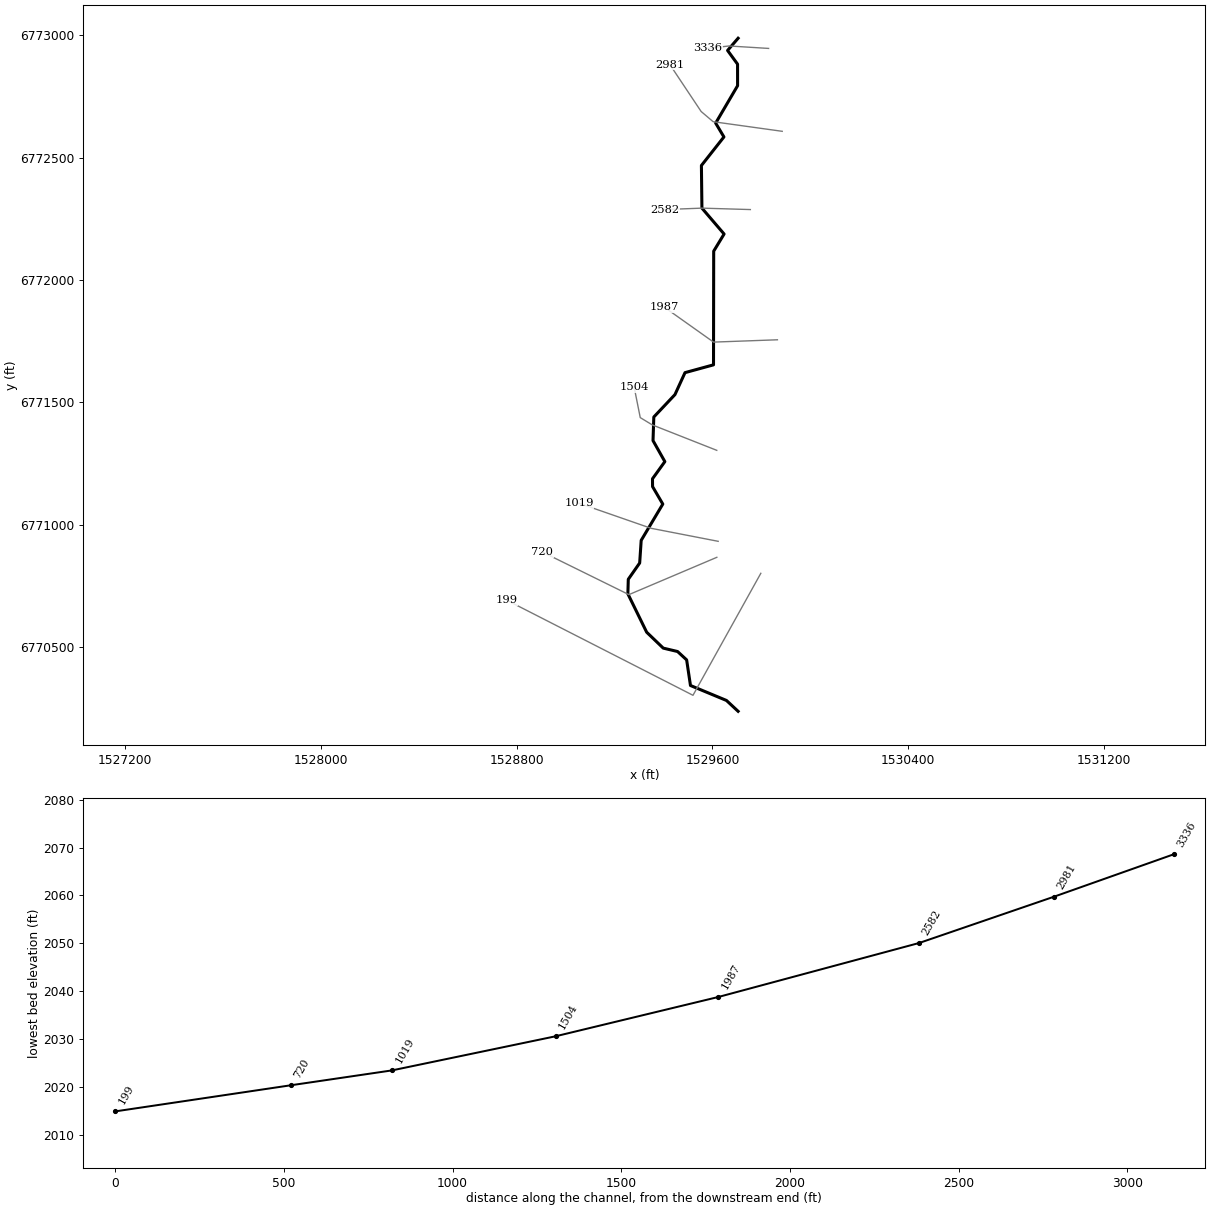
--- Elm 70.prj (project) ---

Proj Title=Elm 70 Base Level Engineering
Current Plan=p01
Default Exp/Contr=0.3,0.1
English Units
Geom File=g01
Flow File=f01
Plan File=p01
BEGIN DESCRIPTION:
Elm 70
END DESCRIPTION:

--- Elm 70.p01 (plan) ---

Plan Title=Multiple Run
Short Identifier=Multiple
Geom File=g01
Flow File=f01
Subcritical Flow
K Sum by GR= 0
Std Step Tol= 0.01
Critical Tol= 0.01
Num of Std Step Trials= 20
Max Error Tol= 0.3
Flow Tol Ratio= 0.001
Split Flow NTrial= 30
Split Flow Tol= 0.02
Split Flow Ratio= 0.02
Log Output Level= 0
Friction Slope Method= 1
Unsteady Friction Slope Method= 2
Unsteady Bridges Friction Slope Method= 1
Parabolic Critical Depth
Global Vel Dist=  1 , 1 , 1
Global Log Level= 0
CheckData=True
Encroach Param= -1, 0, 0, 0
BEGIN DESCRIPTION:
Multiple Run
END DESCRIPTION:

--- Elm 70.f01 (steady flow) ---

Flow Title=Multiple
Number of Profiles=7
Profile Names=10-year,25-year,50-year,1pct_min,100-year,1pct_plu,500-year
River Rch & RM= Elm 70,Reach-1,3336
     180     248     304     232     373     513     564
River Rch & RM= Elm 70,Reach-1,1019
     212     295     365     280     449     618     689
Boundary for River Rch & Prof#=Elm 70,Reach-1,1
Up Type=0
Dn Type=3
Dn Slope=0.005
Boundary for River Rch & Prof#=Elm 70,Reach-1,2
Up Type=0
Dn Type=3
Dn Slope=0.005
Boundary for River Rch & Prof#=Elm 70,Reach-1,3
Up Type=0
Dn Type=3
Dn Slope=0.005
Boundary for River Rch & Prof#=Elm 70,Reach-1,4
Up Type=0
Dn Type=3
Dn Slope=0.005
Boundary for River Rch & Prof#=Elm 70,Reach-1,5
Up Type=0
Dn Type=3
Dn Slope=0.005
Boundary for River Rch & Prof#=Elm 70,Reach-1,6
Up Type=0
Dn Type=3
Dn Slope=0.005
Boundary for River Rch & Prof#=Elm 70,Reach-1,7
Up Type=0
Dn Type=3
Dn Slope=0.005

--- Elm 70.g01 (geometry) ---

Geom Title=Existing Conditions

River Reach=Elm 70,Reach-1
Reach XY= 30
      1529705.00      6772988.00      1529661.91      6772938.14
      1529702.73      6772882.12      1529702.85      6772793.97
      1529613.25      6772641.23      1529646.99      6772584.67
      1529554.96      6772468.02      1529557.07      6772293.85
      1529647.67      6772188.10      1529605.19      6772118.02
      1529604.44      6771653.58      1529487.90      6771621.69
      1529446.81      6771531.98      1529360.41      6771440.42
      1529357.18      6771343.96      1529405.55      6771258.21
      1529355.00      6771188.00      1529355.31      6771156.12
      1529397.15      6771084.72      1529308.83      6770936.42
      1529302.64      6770843.97      1529256.10      6770777.45
      1529254.40      6770717.95      1529331.27      6770561.12
      1529398.95      6770496.16      1529457.57      6770482.26
      1529494.60      6770448.06      1529510.25      6770343.44
      1529657.36      6770282.32      1529705.00      6770238.00

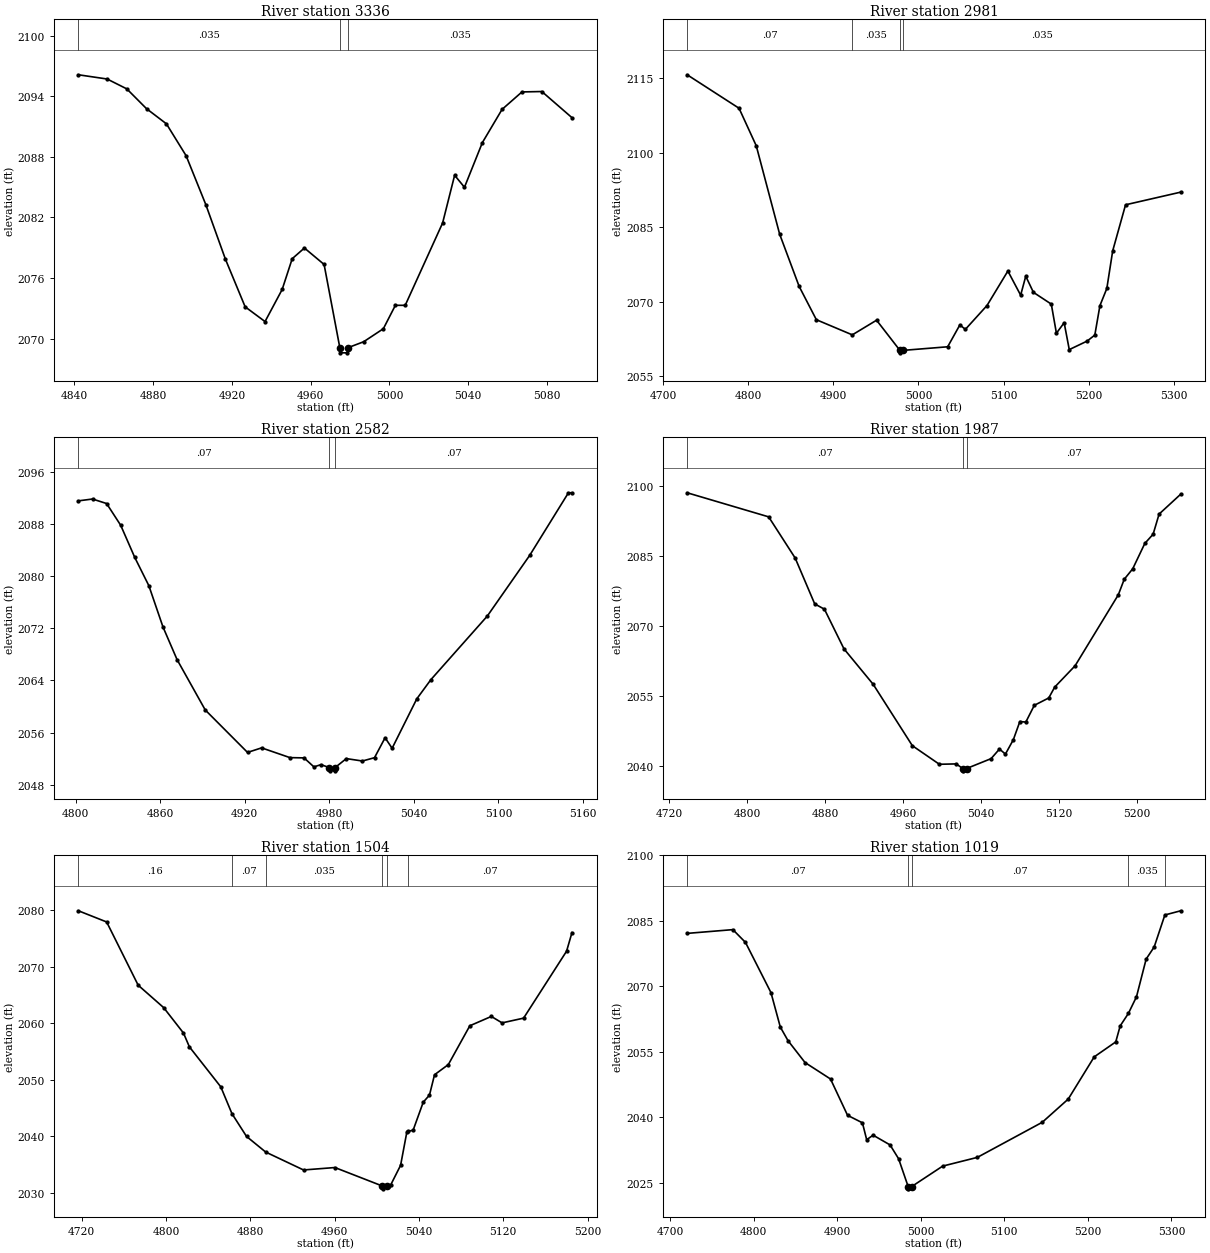
Type RM Length L Ch R = 1,3336,355,355,355
BEGIN DESCRIPTION:
436
END DESCRIPTION:
XS GIS Cut Line= 3
      1529829.58      6772946.38      1529667.86      6772956.38
      1529579.75      6772946.41
#Sta/Elev= 30
  4842.0 2096.14  4856.6 2095.72  4866.6 2094.74  4876.6 2092.78  4886.7 2091.28
  4896.7 2088.12  4906.7 2083.28  4916.7 2077.85  4926.7 2073.14  4936.8 2071.68
  4945.5 2074.86  4950.6 2077.91  4956.8 2078.97  4966.8 2077.34  4974.8 2069.08
  4975.1 2068.58  4978.6 2068.58  4978.8 2069.08  4986.9 2069.68  4996.9 2070.97
  5003.0 2073.29  5008.0 2073.29  5027.0 2081.45  5033.1 2086.18  5038.1 2084.99
  5047.2 2089.42  5057.2 2092.71  5067.3 2094.44  5077.4 2094.48  5092.7 2091.89
#Mann=3,-1,0
  4842.0   0.035       0  4974.8   0.035       0  4978.8   0.035       0
Bank Sta=4974.8,4978.8
Exp/Cntr=0.3,0.1

Type RM Length L Ch R = 1,2981,399,399,399
BEGIN DESCRIPTION:
799
END DESCRIPTION:
XS GIS Cut Line= 4
      1529885.28      6772607.71      1529602.95      6772647.00
      1529553.85      6772688.73      1529426.21      6772880.19
#Sta/Elev= 30
  4728.4 2115.73  4789.3 2108.99  4809.5 2101.44  4837.0 2083.63  4859.9 2073.11
  4880.1 2066.41  4922.3 2063.36  4950.8 2066.31  4978.2 2060.24  4978.5 2059.74
  4982.2 2060.24  5034.3 2060.96  5048.6 2065.36  5055.1 2064.47  5080.5 2069.27
  5105.0 2076.21  5120.0 2071.35  5126.0 2075.17  5135.0 2071.92  5156.0 2069.55
  5162.0 2063.69  5171.1 2065.80  5177.1 2060.39  5198.1 2062.11  5207.1 2063.32
  5213.1 2069.25  5221.2 2072.70  5228.1 2080.28  5243.2 2089.55  5308.0 2092.10
#Mann=4,-1,0
  4728.4    0.07       0  4922.3   0.035       0  4978.2   0.035       0
  4982.2   0.035       0
Bank Sta=4978.2,4982.2
Exp/Cntr=0.3,0.1

Type RM Length L Ch R = 1,2582,595,595,595
BEGIN DESCRIPTION:
435
END DESCRIPTION:
XS GIS Cut Line= 3
      1529754.99      6772288.00      1529557.07      6772293.85
      1529404.99      6772288.00
#Sta/Elev= 30
  4802.0 2091.59  4812.0 2091.87  4822.0 2091.18  4832.0 2087.84  4842.0 2082.89
  4852.0 2078.55  4862.0 2072.22  4872.0 2067.20  4892.0 2059.46  4922.0 2052.94
  4932.0 2053.64  4952.1 2052.14  4962.1 2052.10  4969.1 2050.72  4974.1 2051.06
  4980.1 2050.61  4980.3 2050.11  4983.8 2050.11  4984.1 2050.61  4992.1 2051.99
  5003.5 2051.62  5012.1 2052.13  5019.6 2055.19  5024.6 2053.58  5042.1 2061.17
  5052.1 2064.12  5092.1 2073.88  5122.2 2083.21  5149.7 2092.83  5152.2 2092.83
#Mann=3,-1,0
  4802.0    0.07       0  4980.1    0.07       0  4984.1    0.07       0
Bank Sta=4980.1,4984.1
Exp/Cntr=0.3,0.1

Type RM Length L Ch R = 1,1987,483,483,483
BEGIN DESCRIPTION:
434
END DESCRIPTION:
XS GIS Cut Line= 3
      1529865.62      6771755.95      1529604.59      6771746.47
      1529404.98      6771888.01
#Sta/Elev= 30
  4738.8 2098.58  4822.3 2093.41  4849.5 2084.56  4869.5 2074.72  4879.5 2073.57
  4899.5 2065.06  4929.5 2057.43  4969.6 2044.26  4997.3 2040.27  5014.6 2040.35
  5021.2 2039.36  5021.5 2038.86  5025.2 2039.36  5050.3 2041.48  5058.9 2043.54
  5065.0 2042.46  5073.1 2045.54  5079.8 2049.45  5085.9 2049.33  5094.6 2052.93
  5109.4 2054.51  5115.5 2056.84  5136.4 2061.42  5180.7 2076.66  5186.8 2080.01
  5195.5 2082.26  5207.9 2087.71  5216.4 2089.68  5222.5 2094.00  5244.7 2098.28
#Mann=3,-1,0
  4738.8    0.07       0  5021.2    0.07       0  5025.2    0.07       0
Bank Sta=5021.2,5025.2
Exp/Cntr=0.3,0.1

Type RM Length L Ch R = 1,1504,485,485,485
BEGIN DESCRIPTION:
433
END DESCRIPTION:
XS GIS Cut Line= 4
      1529617.71      6771304.27      1529354.33      6771408.08
      1529305.00      6771438.00      1529279.99      6771563.03
#Sta/Elev= 30
  4716.9 2079.87  4743.7 2077.89  4773.6 2066.70  4797.8 2062.73  4816.6 2058.23
  4822.2 2055.79  4852.0 2048.71  4862.6 2043.96  4876.4 2039.94  4894.6 2037.17
  4930.5 2034.00  4960.3 2034.43  5005.3 2031.16  5005.5 2030.66  5009.3 2031.16
  5013.1 2031.31  5022.6 2034.82  5028.6 2040.78  5030.1 2040.85  5034.5 2041.04
  5044.1 2046.00  5050.0 2047.25  5054.8 2050.85  5067.9 2052.65  5088.3 2059.52
  5108.7 2061.17  5118.9 2060.03  5139.3 2060.87  5180.1 2072.72  5185.2 2076.00
#Mann=6,-1,0
  4716.9    0.16       0  4862.6    0.07       0  4894.6   0.035       0
  5005.3   0.035       0  5009.3   0.035       0  5030.1    0.07       0
Bank Sta=5005.3,5009.3
Exp/Cntr=0.3,0.1

Type RM Length L Ch R = 1,1019,299,299,299
BEGIN DESCRIPTION:
432
END DESCRIPTION:
XS GIS Cut Line= 3
      1529623.49      6770932.56      1529348.91      6770985.83
      1529054.97      6771088.01
#Sta/Elev= 30
  4720.3 2082.09  4775.0 2082.95  4790.1 2080.02  4820.6 2068.52  4831.8 2060.62
  4841.0 2057.51  4861.4 2052.49  4891.9 2048.72  4912.3 2040.40  4930.1 2038.68
  4935.2 2034.81  4942.9 2035.85  4963.2 2033.61  4973.4 2030.45  4984.9 2024.05
  4985.2 2023.55  4988.9 2024.05  5026.2 2028.76  5067.7 2030.76  5145.4 2038.80
  5176.5 2044.12  5207.6 2053.79  5233.4 2057.22  5238.7 2060.89  5248.5 2063.74
  5258.2 2067.55  5269.8 2076.21  5279.4 2078.97  5292.2 2086.31  5311.2 2087.27
#Mann=5,-1,0
  4720.3    0.07       0  4984.9    0.07       0  4988.9    0.07       0
  5248.5   0.035       0  5292.2    0.07       0
Bank Sta=4984.9,4988.9
Exp/Cntr=0.3,0.1

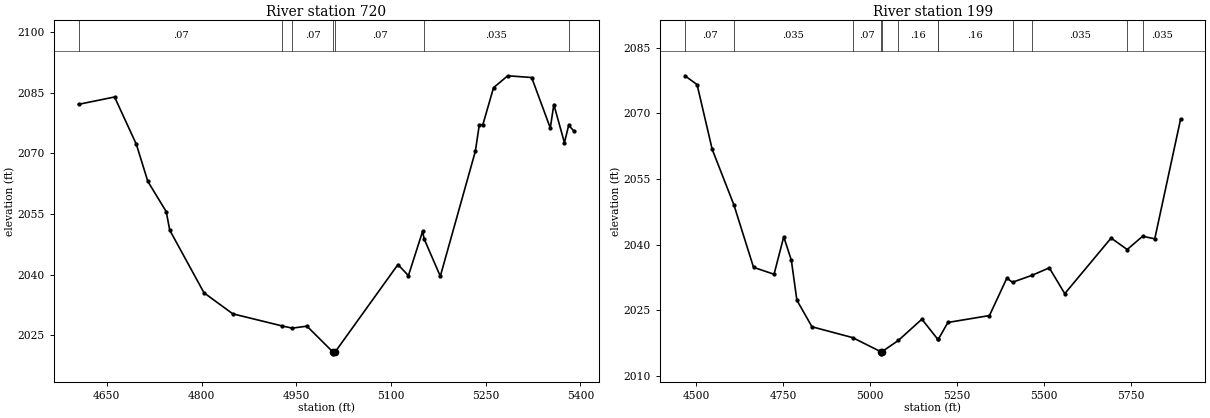
Type RM Length L Ch R = 1,720,521,521,521
BEGIN DESCRIPTION:
796
END DESCRIPTION:
XS GIS Cut Line= 3
      1529618.02      6770867.19      1529258.60      6770714.71
      1528904.60      6770888.98
#Sta/Elev= 30
  4605.1 2082.11  4662.2 2083.93  4696.7 2072.23  4714.9 2063.06  4744.0 2055.61
  4749.6 2051.02  4803.9 2035.53  4849.5 2030.34  4928.0 2027.34  4943.6 2026.81
  4966.9 2027.30  5007.7 2020.96  5008.0 2020.46  5011.7 2020.96  5111.0 2042.52
  5127.6 2039.79  5150.1 2050.75  5152.4 2048.90  5178.1 2039.63  5233.6 2070.51
  5239.9 2077.08  5245.5 2077.09  5262.4 2086.23  5284.9 2089.17  5322.8 2088.74
  5352.3 2076.26  5357.9 2082.07  5374.7 2072.62  5381.4 2076.94  5390.1 2075.46
#Mann=7,-1,0
  4605.1    0.07       0  4928.0    0.16       0  4943.6    0.07       0
  5007.7    0.07       0  5011.7    0.07       0  5152.4   0.035       0
  5381.4    0.07       0
Bank Sta=5007.7,5011.7
Exp/Cntr=0.3,0.1

Type RM Length L Ch R = 1,199,0,0,0
BEGIN DESCRIPTION:
431
END DESCRIPTION:
XS GIS Cut Line= 3
      1529797.80      6770801.88      1529520.54      6770303.42
      1528758.75      6770692.31
#Sta/Elev= 30
  4467.2 2078.63  4502.0 2076.61  4545.5 2061.80  4608.1 2049.05  4664.4 2034.80
  4723.4 2033.22  4751.3 2041.78  4773.1 2036.45  4789.1 2027.28  4832.5 2021.20
  4949.5 2018.72  5030.1 2015.51  5030.4 2015.01  5034.1 2015.51  5081.0 2018.08
  5148.6 2022.94  5193.7 2018.40  5195.8 2018.32  5223.4 2022.19  5343.0 2023.77
  5393.0 2032.32  5409.3 2031.39  5466.5 2033.01  5515.1 2034.69  5559.6 2028.78
  5692.9 2041.50  5739.2 2038.88  5783.6 2041.91  5818.5 2041.33  5892.9 2068.75
#Mann=12,-1,0
  4467.2    0.07       0  4608.1   0.035       0  4949.5    0.07       0
  5030.1    0.07       0  5034.1    0.07       0  5081.0    0.16       0
  5193.7   0.035       0  5195.8    0.16       0  5409.3    0.07       0
  5466.5   0.035       0  5739.2    0.07       0  5783.6   0.035       0
Bank Sta=5030.1,5034.1
Exp/Cntr=0.3,0.1

Chan Stop Cuts=-1