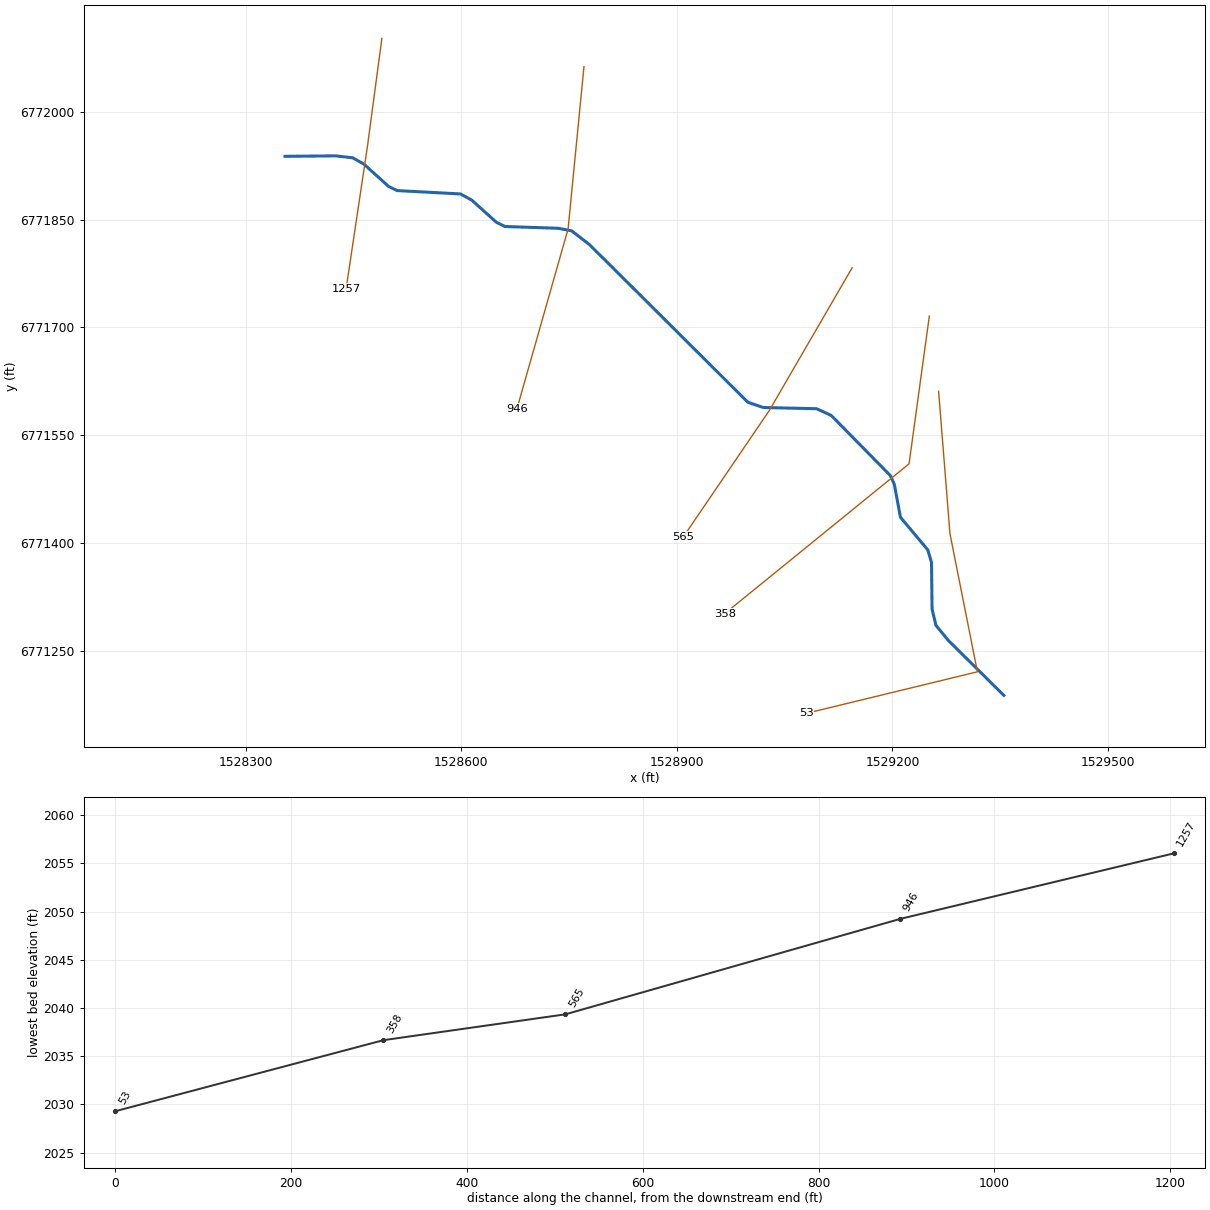
--- Elm 71.prj (project) ---

Proj Title=Elm 71 Base Level Engineering
Current Plan=p01
Default Exp/Contr=0.3,0.1
English Units
Geom File=g01
Flow File=f01
Plan File=p01
BEGIN DESCRIPTION:
Elm 71
END DESCRIPTION:

--- Elm 71.p01 (plan) ---

Plan Title=Multiple Run
Short Identifier=Multiple
Geom File=g01
Flow File=f01
Subcritical Flow
K Sum by GR= 0
Std Step Tol= 0.01
Critical Tol= 0.01
Num of Std Step Trials= 20
Max Error Tol= 0.3
Flow Tol Ratio= 0.001
Split Flow NTrial= 30
Split Flow Tol= 0.02
Split Flow Ratio= 0.02
Log Output Level= 0
Friction Slope Method= 1
Unsteady Friction Slope Method= 2
Unsteady Bridges Friction Slope Method= 1
Parabolic Critical Depth
Global Vel Dist=  1 , 1 , 1
Global Log Level= 0
CheckData=True
Encroach Param= -1, 0, 0, 0
BEGIN DESCRIPTION:
Multiple Run
END DESCRIPTION:

--- Elm 71.f01 (steady flow) ---

Flow Title=Multiple
Number of Profiles=7
Profile Names=10-year,25-year,50-year,1pct_min,100-year,1pct_plu,500-year
River Rch & RM= Elm 71,Reach-1,1257
      59      75      87      63     101     139     139
Boundary for River Rch & Prof#=Elm 71,Reach-1,1
Up Type=0
Dn Type=3
Dn Slope=0.005
Boundary for River Rch & Prof#=Elm 71,Reach-1,2
Up Type=0
Dn Type=3
Dn Slope=0.005
Boundary for River Rch & Prof#=Elm 71,Reach-1,3
Up Type=0
Dn Type=3
Dn Slope=0.005
Boundary for River Rch & Prof#=Elm 71,Reach-1,4
Up Type=0
Dn Type=3
Dn Slope=0.005
Boundary for River Rch & Prof#=Elm 71,Reach-1,5
Up Type=0
Dn Type=3
Dn Slope=0.005
Boundary for River Rch & Prof#=Elm 71,Reach-1,6
Up Type=0
Dn Type=3
Dn Slope=0.005
Boundary for River Rch & Prof#=Elm 71,Reach-1,7
Up Type=0
Dn Type=3
Dn Slope=0.005

--- Elm 71.g01 (geometry) ---

Geom Title=Existing Conditions

River Reach=Elm 71,Reach-1
Reach XY= 30
      1528355.00      6771938.00      1528425.26      6771938.64
      1528449.13      6771935.90      1528464.65      6771927.15
      1528498.95      6771896.15      1528510.97      6771890.33
      1528599.03      6771885.65      1528614.63      6771877.11
      1528648.96      6771846.19      1528660.98      6771840.36
      1528734.95      6771837.87      1528753.50      6771834.39
      1528778.52      6771815.12      1528833.60      6771760.31
      1528888.68      6771705.49      1528998.83      6771595.86
      1529020.22      6771588.53      1529094.52      6771586.84
      1529114.81      6771577.49      1529155.84      6771535.78
      1529196.87      6771494.08      1529202.51      6771481.98
      1529211.14      6771435.83      1529249.23      6771390.32
      1529254.35      6771372.73      1529255.12      6771308.05
      1529260.46      6771285.55      1529277.77      6771264.43
      1529316.38      6771226.22      1529355.00      6771188.00

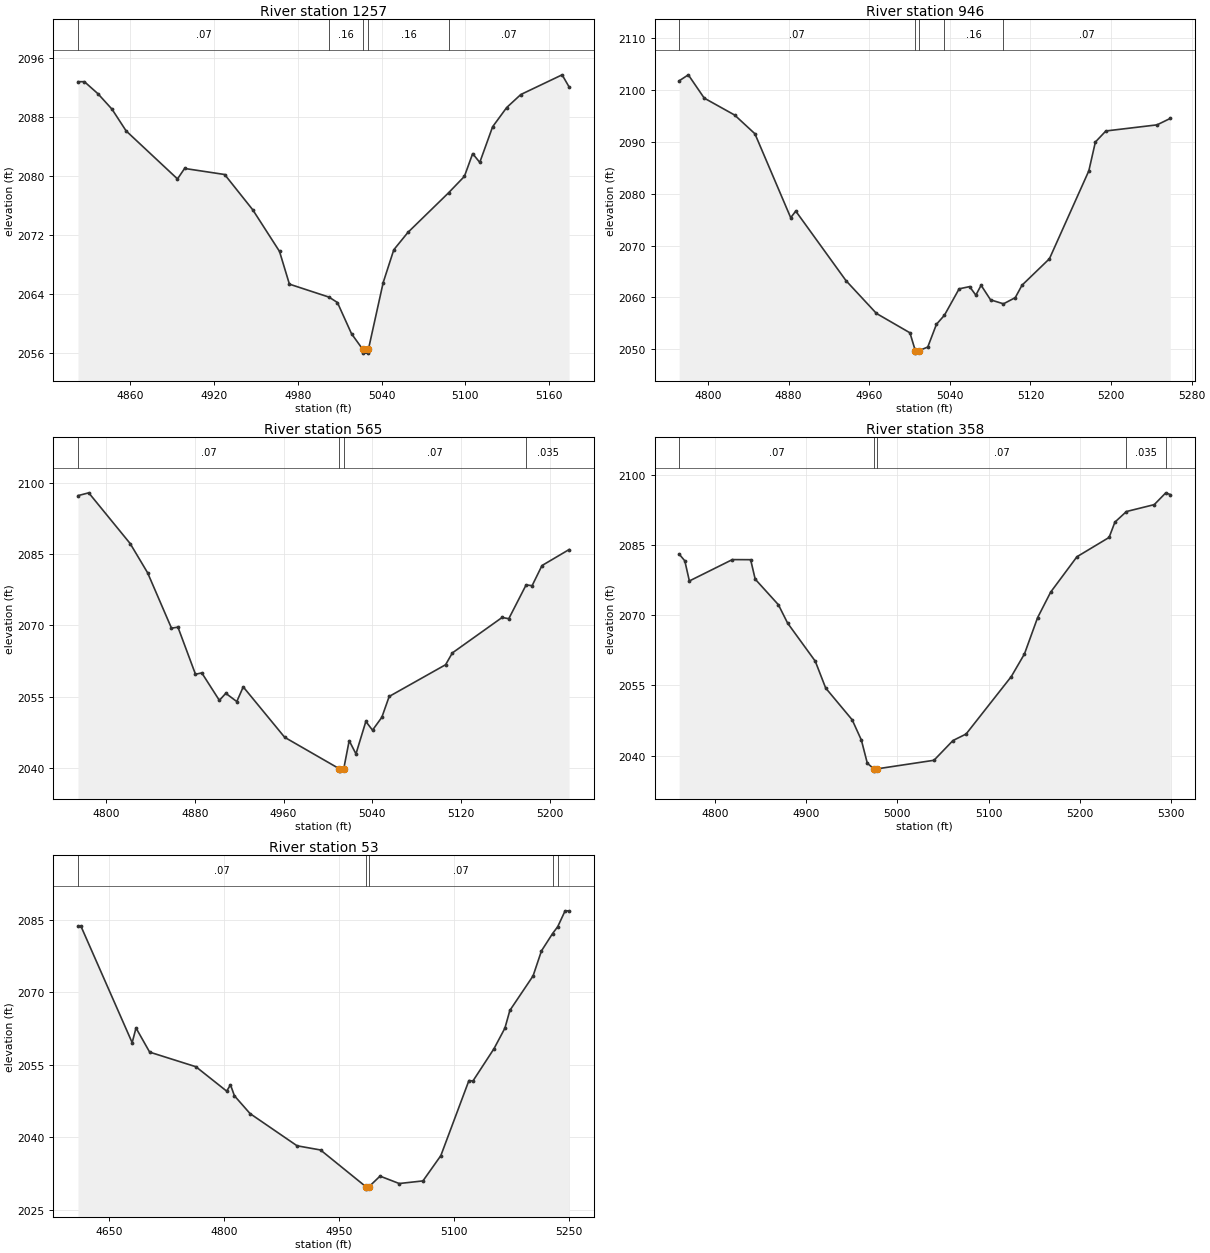
Type RM Length L Ch R = 1,1257,311,311,311
BEGIN DESCRIPTION:
476
END DESCRIPTION:
XS GIS Cut Line= 3
      1528489.65      6772102.15      1528469.60      6771952.02
      1528439.89      6771753.80
#Sta/Elev= 30
  4822.4 2092.83  4827.0 2092.83  4836.7 2091.20  4846.8 2089.10  4856.9 2086.16
  4893.7 2079.65  4898.8 2081.07  4927.5 2080.25  4947.7 2075.45  4966.8 2069.83
  4973.9 2065.39  5002.3 2063.63  5008.3 2062.90  5018.4 2058.67  5026.5 2056.54
  5026.7 2056.04  5030.2 2056.04  5030.5 2056.54  5041.1 2065.61  5048.7 2070.05
  5058.8 2072.40  5088.0 2077.78  5099.3 2080.00  5105.2 2083.08  5110.3 2081.89
  5119.5 2086.72  5129.6 2089.33  5139.7 2091.09  5169.3 2093.76  5174.3 2092.12
#Mann=5,-1,0
  4822.4    0.07       0  5002.3    0.16       0  5026.5    0.07       0
  5030.5    0.16       0  5088.0    0.07       0
Bank Sta=5026.5,5030.5
Exp/Cntr=0.3,0.1

Type RM Length L Ch R = 1,946,381,381,381
BEGIN DESCRIPTION:
798
END DESCRIPTION:
XS GIS Cut Line= 3
      1528770.82      6772062.83      1528748.72      6771836.95
      1528677.52      6771586.53
#Sta/Elev= 30
  4771.4 2101.77  4780.5 2102.93  4796.3 2098.44  4826.5 2095.17  4846.6 2091.56
  4882.1 2075.37  4887.1 2076.65  4937.0 2063.22  4967.2 2056.90  5000.4 2053.17
  5005.7 2049.75  5005.9 2049.25  5009.7 2049.75  5018.1 2050.43  5026.7 2054.81
  5034.6 2056.55  5049.2 2061.65  5059.6 2062.08  5065.8 2060.43  5071.0 2062.34
  5080.4 2059.53  5093.2 2058.76  5104.9 2059.95  5111.6 2062.35  5138.8 2067.45
  5177.9 2084.41  5184.4 2089.97  5194.8 2092.10  5245.6 2093.28  5258.7 2094.52
#Mann=5,-1,0
  4771.4    0.07       0  5005.7    0.07       0  5009.7    0.07       0
  5034.6    0.16       0  5093.2    0.07       0
Bank Sta=5005.7,5009.7
Exp/Cntr=0.3,0.1

Type RM Length L Ch R = 1,565,207,207,207
BEGIN DESCRIPTION:
797
END DESCRIPTION:
XS GIS Cut Line= 3
      1529143.94      6771782.98      1529028.55      6771584.12
      1528909.11      6771408.62
#Sta/Elev= 30
  4774.9 2097.24  4784.6 2097.83  4821.9 2087.17  4837.6 2081.03  4859.1 2069.39
  4864.9 2069.61  4880.7 2059.71  4886.4 2059.99  4902.2 2054.22  4908.0 2055.70
  4917.9 2053.97  4923.7 2057.05  4961.0 2046.46  5010.2 2039.85  5010.5 2039.35
  5014.2 2039.85  5019.1 2045.75  5025.2 2042.97  5034.1 2049.79  5040.1 2047.96
  5048.5 2050.66  5055.1 2055.04  5105.9 2061.71  5112.0 2064.19  5156.8 2071.64
  5162.8 2071.38  5178.4 2078.48  5183.8 2078.32  5192.7 2082.55  5217.1 2085.91
#Mann=4,-1,0
  4774.9    0.07       0  5010.2    0.07       0  5014.2    0.07       0
  5178.4   0.035       0
Bank Sta=5010.2,5014.2
Exp/Cntr=0.3,0.1

Type RM Length L Ch R = 1,358,305,305,305
BEGIN DESCRIPTION:
865
END DESCRIPTION:
XS GIS Cut Line= 3
      1529251.31      6771715.72      1529223.09      6771510.16
      1528966.65      6771301.80
#Sta/Elev= 30
  4761.0 2083.09  4767.2 2081.65  4772.2 2077.34  4819.3 2081.91  4839.3 2081.89
  4844.3 2077.73  4869.7 2072.26  4879.8 2068.33  4910.1 2060.18  4921.5 2054.44
  4950.5 2047.65  4960.6 2043.31  4967.1 2038.36  4974.2 2037.17  4974.4 2036.67
  4978.2 2037.17  5040.1 2038.99  5060.9 2043.21  5075.3 2044.61  5124.8 2056.90
  5139.2 2061.73  5153.6 2069.49  5167.9 2074.95  5196.7 2082.52  5231.9 2086.65
  5238.3 2089.93  5250.9 2092.19  5281.4 2093.67  5294.0 2096.19  5298.9 2095.82
#Mann=5,-1,0
  4761.0    0.07       0  4974.2    0.07       0  4978.2    0.07       0
  5250.9   0.035       0  5294.0    0.07       0
Bank Sta=4974.2,4978.2
Exp/Cntr=0.3,0.1

Type RM Length L Ch R = 1,53,0,0,0
BEGIN DESCRIPTION:
475
END DESCRIPTION:
XS GIS Cut Line= 4
      1529264.20      6771611.09      1529280.00      6771413.00
      1529318.20      6771220.83      1529079.97      6771162.99
#Sta/Elev= 30
  4609.9 2083.66  4613.9 2083.66  4680.5 2059.61  4685.5 2062.65  4703.3 2057.65
  4763.5 2054.63  4803.6 2049.58  4808.6 2050.88  4813.7 2048.62  4834.1 2044.93
  4895.3 2038.27  4925.9 2037.40  4985.0 2029.80  4985.3 2029.30  4989.0 2029.80
  5003.4 2031.99  5028.4 2030.46  5059.3 2031.00  5082.6 2036.23  5119.2 2051.77
  5124.4 2051.67  5151.9 2058.37  5166.1 2062.62  5172.5 2066.27  5202.8 2073.43
  5213.7 2078.60  5228.1 2082.17  5234.9 2083.61  5244.5 2086.89  5249.7 2086.89
#Mann=5,-1,0
  4609.9    0.07       0  4985.0    0.07       0  4989.0    0.07       0
  5228.1   0.035       0  5234.9    0.07       0
Bank Sta=4985,4989
Exp/Cntr=0.3,0.1

Chan Stop Cuts=-1