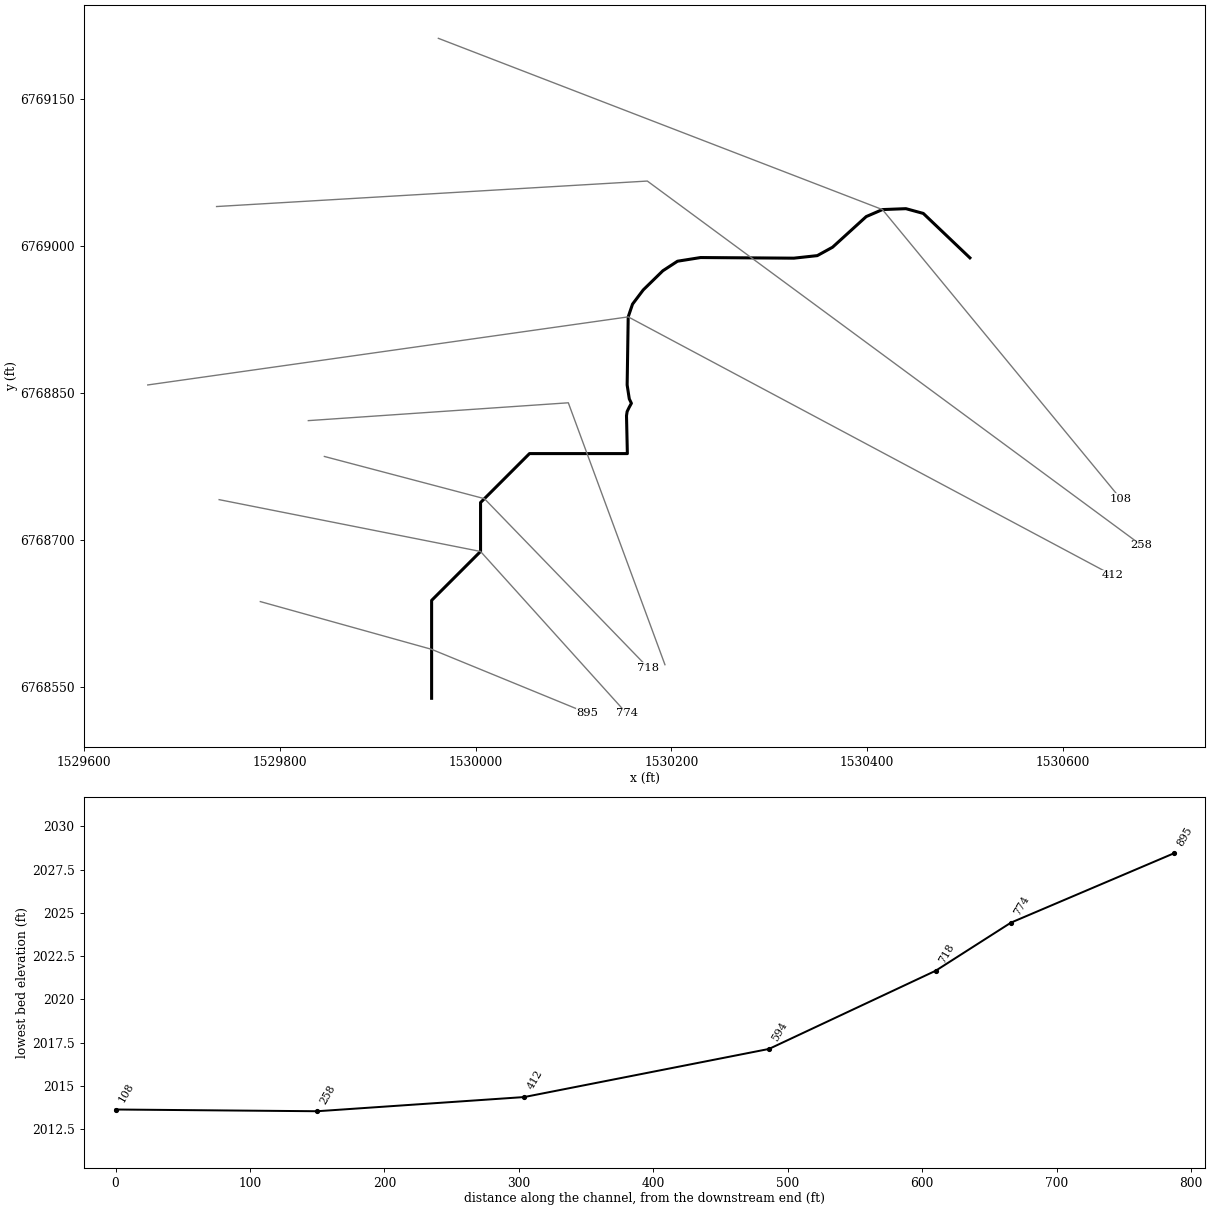
--- Elm 72.prj (project) ---

Proj Title=Elm 72 Base Level Engineering
Current Plan=p01
Default Exp/Contr=0.3,0.1
English Units
Geom File=g01
Flow File=f01
Plan File=p01
BEGIN DESCRIPTION:
Elm 72
END DESCRIPTION:

--- Elm 72.p01 (plan) ---

Plan Title=Multiple Run
Short Identifier=Multiple
Geom File=g01
Flow File=f01
Subcritical Flow
K Sum by GR= 0
Std Step Tol= 0.01
Critical Tol= 0.01
Num of Std Step Trials= 20
Max Error Tol= 0.3
Flow Tol Ratio= 0.001
Split Flow NTrial= 30
Split Flow Tol= 0.02
Split Flow Ratio= 0.02
Log Output Level= 0
Friction Slope Method= 1
Unsteady Friction Slope Method= 2
Unsteady Bridges Friction Slope Method= 1
Parabolic Critical Depth
Global Vel Dist=  1 , 1 , 1
Global Log Level= 0
CheckData=True
Encroach Param= -1, 0, 0, 0
BEGIN DESCRIPTION:
Multiple Run
END DESCRIPTION:

--- Elm 72.f01 (steady flow) ---

Flow Title=Multiple
Number of Profiles=7
Profile Names=10-year,25-year,50-year,1pct_min,100-year,1pct_plu,500-year
River Rch & RM= Elm 72,Reach-1,895
      95     125     149     111     178     245     255
River Rch & RM= Elm 72,Reach-1,412
     158     216     264     201     322     444     485
Boundary for River Rch & Prof#=Elm 72,Reach-1,1
Up Type=0
Dn Type=3
Dn Slope=0.005
Boundary for River Rch & Prof#=Elm 72,Reach-1,2
Up Type=0
Dn Type=3
Dn Slope=0.005
Boundary for River Rch & Prof#=Elm 72,Reach-1,3
Up Type=0
Dn Type=3
Dn Slope=0.005
Boundary for River Rch & Prof#=Elm 72,Reach-1,4
Up Type=0
Dn Type=3
Dn Slope=0.005
Boundary for River Rch & Prof#=Elm 72,Reach-1,5
Up Type=0
Dn Type=3
Dn Slope=0.005
Boundary for River Rch & Prof#=Elm 72,Reach-1,6
Up Type=0
Dn Type=3
Dn Slope=0.005
Boundary for River Rch & Prof#=Elm 72,Reach-1,7
Up Type=0
Dn Type=3
Dn Slope=0.005

--- Elm 72.g01 (geometry) ---

Geom Title=Existing Conditions

River Reach=Elm 72,Reach-1
Reach XY= 28
      1529955.00      6768538.00      1529955.00      6768588.00
      1529955.00      6768638.00      1530005.00      6768688.00
      1530005.00      6768738.00      1530055.00      6768788.00
      1530105.00      6768788.00      1530155.00      6768788.00
      1530154.12      6768826.65      1530154.75      6768830.95
      1530156.77      6768835.11      1530159.12      6768839.41
      1530156.96      6768843.90      1530154.78      6768858.06
      1530155.86      6768927.69      1530160.28      6768940.71
      1530171.21      6768955.22      1530191.25      6768974.80
      1530206.22      6768984.56      1530229.79      6768988.31
      1530325.14      6768987.68      1530349.07      6768990.28
      1530364.68      6768998.88      1530399.06      6769030.17
      1530415.63      6769037.32      1530439.60      6769038.25
      1530457.37      6769033.39      1530505.00      6768988.00

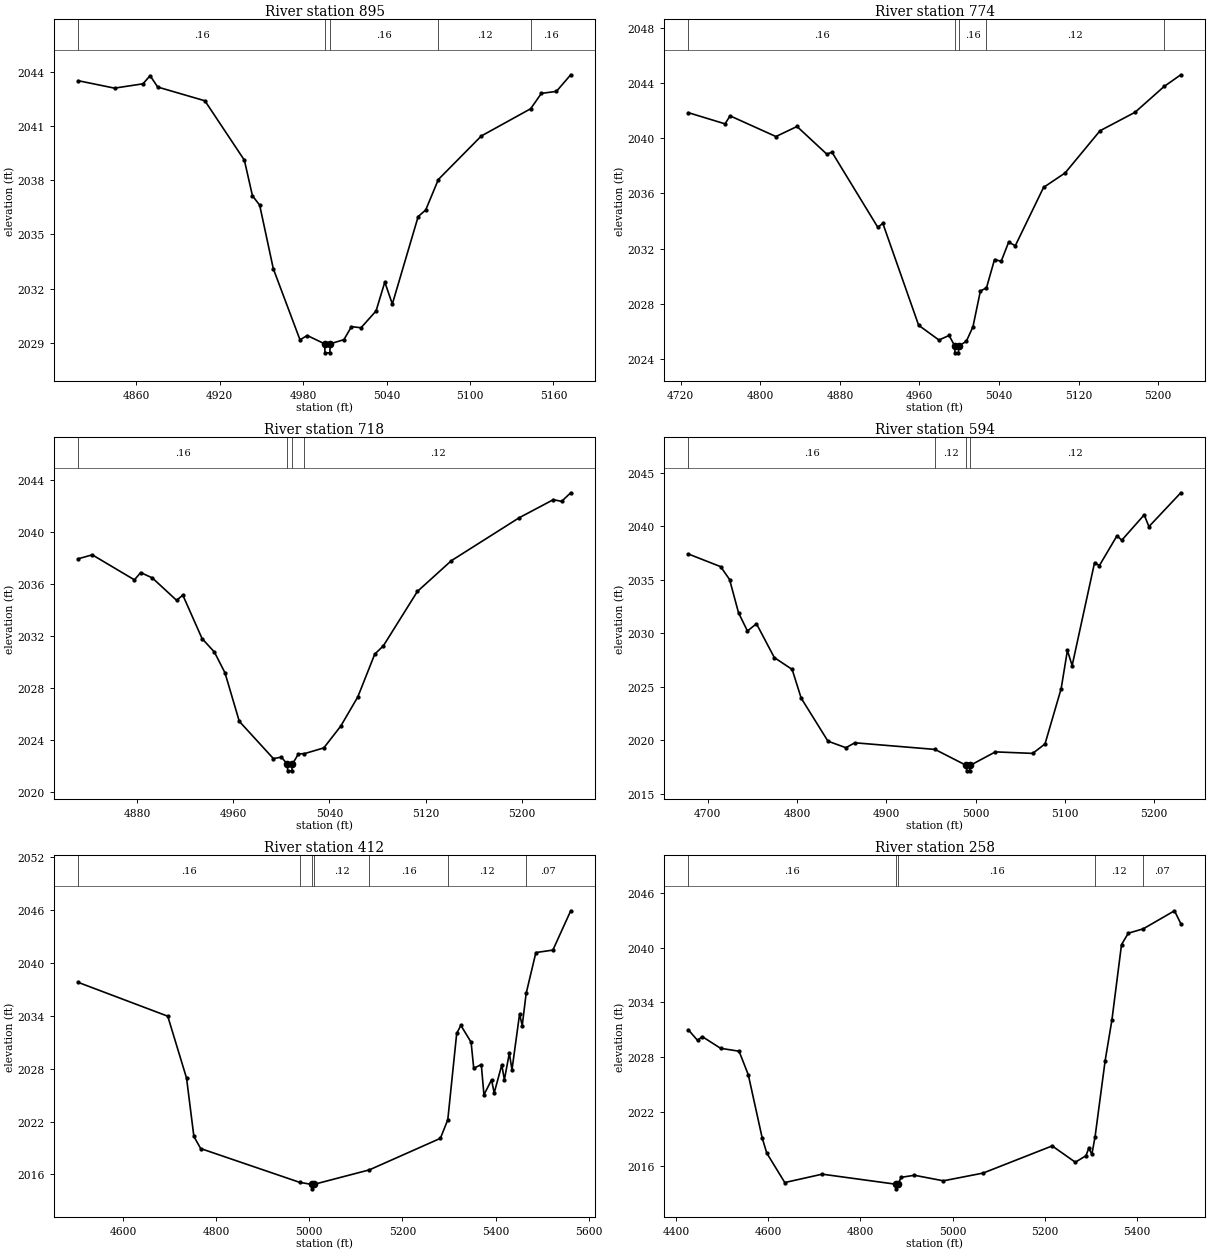
Type RM Length L Ch R = 1,895,121,121,121
BEGIN DESCRIPTION:
Elm 72 4798
END DESCRIPTION:
XS GIS Cut Line= 3
      1529779.97      6768636.79      1529955.00      6768588.00
      1530114.52      6768522.61
#Sta/Elev= 30
  4818.3 2043.51  4844.3 2043.10  4864.8 2043.34  4869.9 2043.79  4875.4 2043.16
  4909.3 2042.40  4937.7 2039.11  4943.5 2037.14  4948.7 2036.62  4958.5 2033.10
  4977.7 2029.16  4982.9 2029.40  4995.4 2028.94  4995.7 2028.44  4999.2 2028.44
  4999.4 2028.94  5009.3 2029.17  5014.7 2029.89  5021.6 2029.83  5032.4 2030.76
  5038.7 2032.36  5044.1 2031.14  5062.7 2035.99  5068.1 2036.35  5077.2 2038.04
  5108.1 2040.45  5143.6 2041.96  5151.3 2042.81  5162.1 2042.92  5172.4 2043.84
#Mann=5,-1,0
  4818.3    0.16       0  4995.4    0.07       0  4999.4    0.16       0
  5077.2    0.12       0  5143.6    0.16       0
Bank Sta=4995.4,4999.4
Exp/Cntr=0.3,0.1

Type RM Length L Ch R = 1,774,56,56,56
BEGIN DESCRIPTION:
Elm 72 4797
END DESCRIPTION:
XS GIS Cut Line= 3
      1529737.90      6768740.95      1530005.00      6768688.00
      1530154.24      6768522.57
#Sta/Elev= 30
  4727.7 2041.86  4764.5 2041.05  4769.6 2041.63  4815.7 2040.13  4836.9 2040.86
  4866.9 2038.85  4872.0 2039.00  4918.1 2033.55  4923.2 2033.83  4959.2 2026.44
  4979.6 2025.37  4989.8 2025.70  4995.5 2024.94  4995.7 2024.44  4999.2 2024.44
  4999.5 2024.94  5007.1 2025.27  5013.8 2026.33  5021.3 2028.93  5027.4 2029.15
  5035.5 2031.21  5042.2 2031.08  5049.7 2032.47  5056.4 2032.21  5084.8 2036.44
  5106.5 2037.49  5141.6 2040.55  5176.8 2041.89  5206.0 2043.76  5222.8 2044.61
#Mann=5,-1,0
  4727.7    0.16       0  4995.5    0.07       0  4999.5    0.16       0
  5027.4    0.12       0  5206.0    0.16       0
Bank Sta=4995.5,4999.5
Exp/Cntr=0.3,0.1

Type RM Length L Ch R = 1,718,124,124,124
BEGIN DESCRIPTION:
Elm 72 4756
END DESCRIPTION:
XS GIS Cut Line= 3
      1529845.43      6768785.07      1530008.94      6768741.94
      1530176.52      6768568.88
#Sta/Elev= 30
  4830.9 2037.93  4842.5 2038.23  4877.6 2036.31  4882.8 2036.87  4892.5 2036.46
  4912.7 2034.74  4917.9 2035.14  4933.9 2031.81  4944.2 2030.77  4953.0 2029.18
  4964.9 2025.46  4993.3 2022.60  5000.0 2022.71  5005.0 2022.16  5005.2 2021.66
  5008.7 2021.66  5009.0 2022.16  5014.2 2022.96  5019.2 2022.98  5035.3 2023.42
  5049.4 2025.09  5063.6 2027.33  5077.7 2030.61  5084.9 2031.25  5113.2 2035.42
  5141.5 2037.78  5198.1 2041.08  5226.4 2042.46  5233.3 2042.33  5240.9 2042.99
#Mann=4,-1,0
  4830.9    0.16       0  5005.0    0.07       0  5009.0    0.16       0
  5019.2    0.12       0
Bank Sta=5005,5009
Exp/Cntr=0.3,0.1

Type RM Length L Ch R = 1,594,182,182,182
BEGIN DESCRIPTION:
Elm 72 4795
END DESCRIPTION:
XS GIS Cut Line= 3
      1529829.02      6768821.68      1530094.67      6768839.91
      1530193.40      6768572.31
#Sta/Elev= 30
  4678.4 2037.39  4714.5 2036.21  4724.5 2035.01  4734.5 2031.91  4744.5 2030.20
  4754.6 2030.88  4774.6 2027.72  4794.6 2026.61  4804.7 2023.93  4834.7 2019.91
  4854.8 2019.30  4864.8 2019.76  4954.6 2019.14  4989.8 2017.64  4990.1 2017.14
  4993.6 2017.14  4993.8 2017.64  5022.2 2018.91  5064.0 2018.77  5077.8 2019.65
  5095.9 2024.82  5102.9 2028.39  5108.2 2026.97  5133.3 2036.58  5138.7 2036.31
  5158.4 2039.09  5163.8 2038.68  5188.9 2041.05  5194.2 2039.95  5229.9 2043.11
#Mann=4,-1,0
  4678.4    0.16       0  4954.6    0.12       0  4989.8    0.07       0
  4993.8    0.12       0
Bank Sta=4989.8,4993.8
Exp/Cntr=0.3,0.1

Type RM Length L Ch R = 1,412,154,154,154
BEGIN DESCRIPTION:
Elm 72 4794
END DESCRIPTION:
XS GIS Cut Line= 3
      1529664.96      6768858.13      1530155.86      6768927.69
      1530650.99      6768663.52
#Sta/Elev= 30
  4504.2 2037.78  4696.1 2033.95  4736.5 2026.92  4752.2 2020.31  4766.8 2018.93
  4979.1 2015.10  5005.3 2014.86  5005.6 2014.36  5009.3 2014.86  5128.8 2016.51
  5281.4 2020.09  5297.3 2022.20  5316.4 2031.99  5325.3 2032.91  5347.3 2031.00
  5353.0 2028.04  5369.2 2028.46  5374.9 2025.03  5391.2 2026.72  5396.9 2025.24
  5413.2 2028.42  5418.8 2026.74  5429.4 2029.75  5435.1 2027.87  5451.4 2034.19
  5457.1 2032.89  5465.5 2036.53  5486.4 2041.17  5522.9 2041.45  5561.2 2045.91
#Mann=7,-1,0
  4504.2    0.16       0  4979.1    0.12       0  5005.3    0.07       0
  5009.3    0.12       0  5128.8    0.16       0  5297.3    0.12       0
  5465.5    0.07       0
Bank Sta=5005.3,5009.3
Exp/Cntr=0.3,0.1

Type RM Length L Ch R = 1,258,150,150,150
BEGIN DESCRIPTION:
Elm 72 4793
END DESCRIPTION:
XS GIS Cut Line= 3
      1529735.28      6769040.43      1530175.40      6769066.47
      1530680.27      6768694.32
#Sta/Elev= 30
  4426.8 2030.98  4446.6 2029.83  4456.6 2030.25  4496.6 2028.96  4536.7 2028.64
  4556.7 2026.05  4586.8 2019.13  4596.8 2017.46  4635.8 2014.23  4717.0 2015.15
  4877.7 2014.04  4877.9 2013.54  4881.7 2014.04  4888.1 2014.80  4916.9 2015.03
  4979.9 2014.42  5066.0 2015.27  5215.9 2018.25  5266.1 2016.46  5289.1 2017.17
  5295.3 2017.99  5302.0 2017.34  5308.9 2019.24  5330.8 2027.61  5345.5 2032.07
  5366.3 2040.34  5381.0 2041.59  5413.5 2042.07  5481.2 2044.05  5494.9 2042.64
#Mann=5,-1,0
  4426.8    0.16       0  4877.7    0.07       0  4881.7    0.16       0
  5308.9    0.12       0  5413.5    0.07       0
Bank Sta=4877.7,4881.7
Exp/Cntr=0.3,0.1

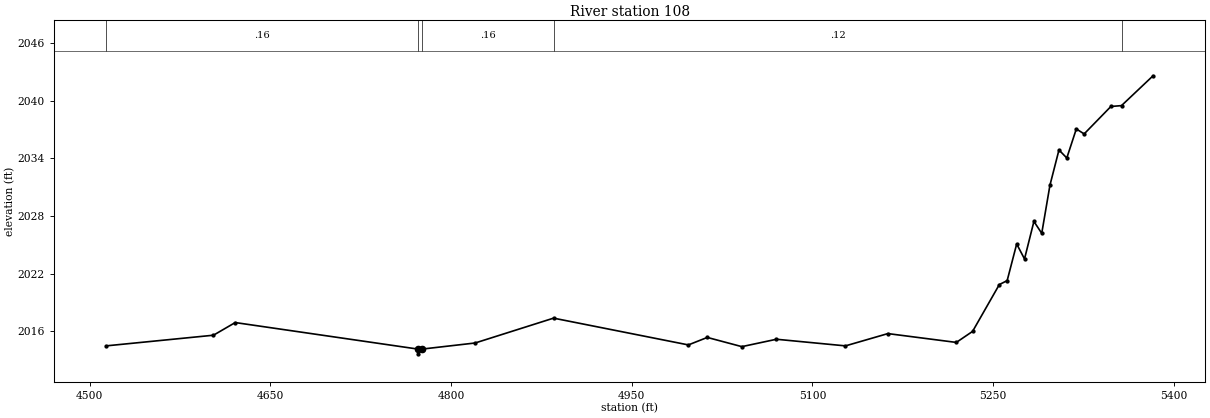
Type RM Length L Ch R = 1,108,0,0,0
BEGIN DESCRIPTION:
Elm 72 4792
END DESCRIPTION:
XS GIS Cut Line= 3
      1529961.90      6769212.29      1530415.63      6769037.32
      1530658.96      6768741.94
#Sta/Elev= 30
  4513.7 2014.47  4602.8 2015.58  4620.9 2016.90  4772.3 2014.14  4772.5 2013.64
  4776.3 2014.14  4820.0 2014.77  4885.1 2017.36  4997.0 2014.57  5012.7 2015.35
  5041.4 2014.39  5070.1 2015.16  5127.4 2014.47  5162.6 2015.75  5219.4 2014.83
  5232.9 2015.98  5255.1 2020.86  5261.6 2021.27  5269.5 2025.09  5276.0 2023.53
  5283.8 2027.44  5290.3 2026.20  5297.1 2031.21  5304.6 2034.89  5311.1 2034.05
  5319.0 2037.08  5325.5 2036.56  5347.7 2039.42  5356.5 2039.51  5382.7 2042.62
#Mann=5,-1,0
  4513.7    0.16       0  4772.3    0.07       0  4776.3    0.16       0
  4885.1    0.12       0  5356.5    0.07       0
Bank Sta=4772.3,4776.3
Exp/Cntr=0.3,0.1

Chan Stop Cuts=-1