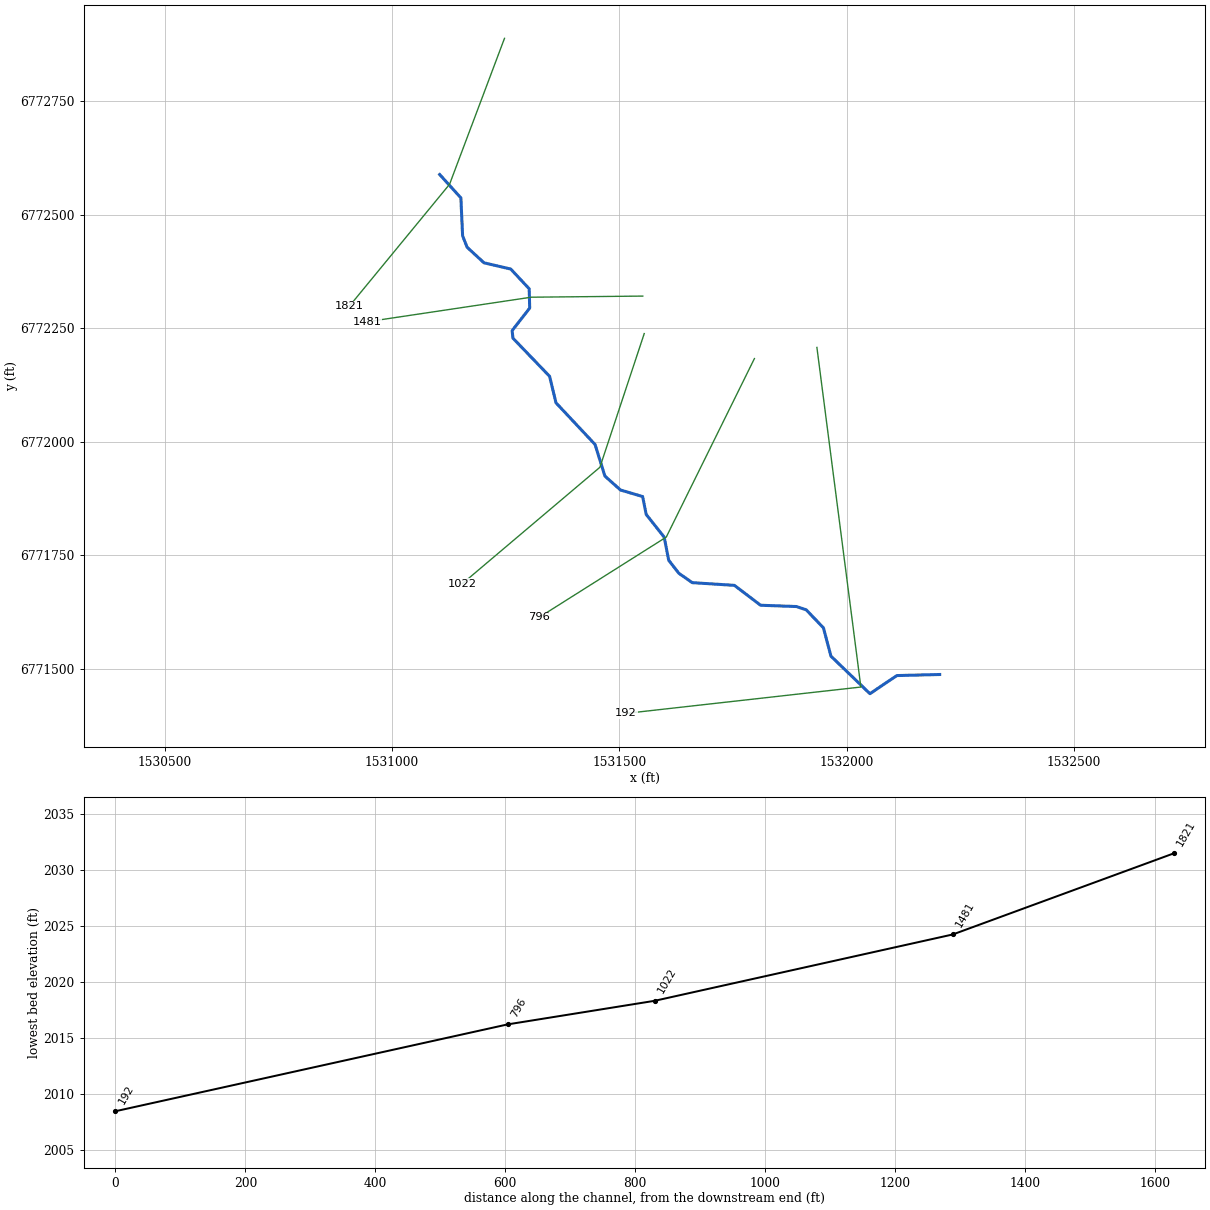
--- Elm 73.prj (project) ---

Proj Title=Elm 73 Base Level Engineering
Current Plan=p01
Default Exp/Contr=0.3,0.1
English Units
Geom File=g01
Flow File=f01
Plan File=p01
BEGIN DESCRIPTION:
Elm 73
END DESCRIPTION:

--- Elm 73.p01 (plan) ---

Plan Title=Multiple Run
Short Identifier=Multiple
Geom File=g01
Flow File=f01
Subcritical Flow
K Sum by GR= 0
Std Step Tol= 0.01
Critical Tol= 0.01
Num of Std Step Trials= 20
Max Error Tol= 0.3
Flow Tol Ratio= 0.001
Split Flow NTrial= 30
Split Flow Tol= 0.02
Split Flow Ratio= 0.02
Log Output Level= 0
Friction Slope Method= 1
Unsteady Friction Slope Method= 2
Unsteady Bridges Friction Slope Method= 1
Parabolic Critical Depth
Global Vel Dist=  1 , 1 , 1
Global Log Level= 0
CheckData=True
Encroach Param= -1, 0, 0, 0
BEGIN DESCRIPTION:
Multiple Run
END DESCRIPTION:

--- Elm 73.f01 (steady flow) ---

Flow Title=Multiple
Number of Profiles=7
Profile Names=10-year,25-year,50-year,1pct_min,100-year,1pct_plu,500-year
River Rch & RM= Elm 73,Reach-1,1821
     158     218     267     204     327     449     495
Boundary for River Rch & Prof#=Elm 73,Reach-1,1
Up Type=0
Dn Type=3
Dn Slope=0.005
Boundary for River Rch & Prof#=Elm 73,Reach-1,2
Up Type=0
Dn Type=3
Dn Slope=0.005
Boundary for River Rch & Prof#=Elm 73,Reach-1,3
Up Type=0
Dn Type=3
Dn Slope=0.005
Boundary for River Rch & Prof#=Elm 73,Reach-1,4
Up Type=0
Dn Type=3
Dn Slope=0.005
Boundary for River Rch & Prof#=Elm 73,Reach-1,5
Up Type=0
Dn Type=3
Dn Slope=0.005
Boundary for River Rch & Prof#=Elm 73,Reach-1,6
Up Type=0
Dn Type=3
Dn Slope=0.005
Boundary for River Rch & Prof#=Elm 73,Reach-1,7
Up Type=0
Dn Type=3
Dn Slope=0.005

--- Elm 73.g01 (geometry) ---

Geom Title=Existing Conditions

River Reach=Elm 73,Reach-1
Reach XY= 30
      1531105.00      6772588.00      1531151.61      6772536.59
      1531155.42      6772453.07      1531165.37      6772427.89
      1531202.46      6772393.75      1531261.40      6772379.95
      1531301.93      6772336.57      1531303.03      6772294.09
      1531264.34      6772244.55      1531266.14      6772227.96
      1531346.80      6772144.05      1531360.87      6772085.72
      1531446.82      6771994.02      1531468.55      6771924.47
      1531502.80      6771893.89      1531551.46      6771879.51
      1531559.34      6771840.09      1531598.90      6771790.20
      1531608.85      6771739.40      1531631.10      6771710.72
      1531660.71      6771690.07      1531753.40      6771684.14
      1531810.98      6771640.36      1531889.91      6771637.53
      1531911.45      6771630.26      1531949.26      6771590.57
      1531965.79      6771528.29      1532051.57      6771445.75
      1532110.77      6771485.65      1532205.00      6771488.00

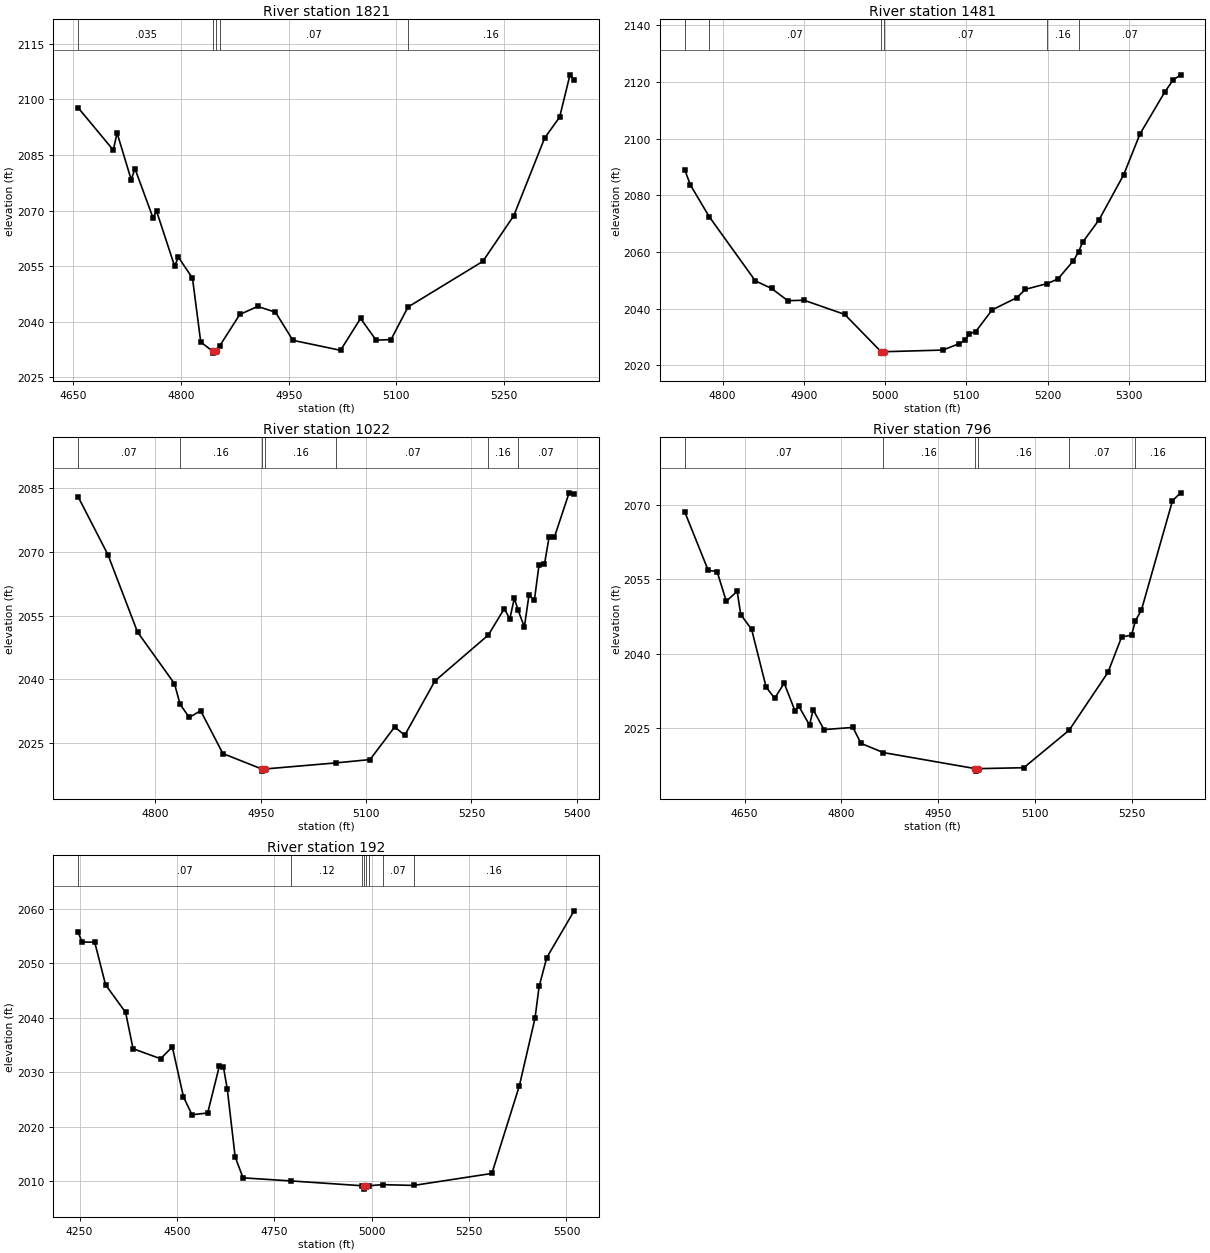
Type RM Length L Ch R = 1,1821,340,340,340
BEGIN DESCRIPTION:
463
END DESCRIPTION:
XS GIS Cut Line= 3
      1531247.59      6772887.58      1531126.73      6772566.48
      1530906.37      6772298.43
#Sta/Elev= 30
  4657.2 2097.72  4706.0 2086.32  4711.3 2090.93  4730.9 2078.33  4736.2 2081.28
  4761.1 2068.11  4766.4 2069.75  4791.3 2055.00  4796.6 2057.39  4816.2 2051.75
  4827.7 2034.49  4844.4 2032.00  4844.7 2031.50  4848.4 2032.00  4854.1 2033.45
  4882.0 2041.93  4906.9 2044.11  4931.7 2042.55  4955.9 2034.96  5022.2 2032.26
  5050.1 2040.87  5071.7 2035.00  5092.5 2035.16  5116.1 2043.95  5220.2 2056.27
  5263.3 2068.60  5306.3 2089.58  5327.1 2095.22  5341.5 2106.63  5347.3 2105.35
#Mann=5,-1,0
  4657.2   0.035       0  4844.4    0.07       0  4848.4   0.035       0
  4854.1    0.07       0  5116.1    0.16       0
Bank Sta=4844.4,4848.4
Exp/Cntr=0.3,0.1

Type RM Length L Ch R = 1,1481,459,459,459
BEGIN DESCRIPTION:
801
END DESCRIPTION:
XS GIS Cut Line= 3
      1531551.94      6772320.52      1531306.49      6772318.07
      1530945.67      6772264.07
#Sta/Elev= 30
  4753.4 2089.05  4760.3 2083.69  4783.5 2072.47  4840.3 2049.79  4860.3 2047.10
  4880.3 2042.78  4900.3 2042.94  4950.3 2037.94  4995.1 2024.77  4995.4 2024.27
  4999.1 2024.77  5071.1 2025.35  5091.4 2027.64  5098.5 2028.78  5103.6 2031.08
  5111.6 2031.89  5131.8 2039.54  5162.1 2043.84  5172.8 2046.80  5199.8 2048.84
  5212.7 2050.45  5231.8 2056.87  5238.2 2060.09  5243.0 2063.36  5263.3 2071.31
  5293.6 2087.21  5313.8 2101.69  5344.2 2116.42  5354.3 2120.62  5363.7 2122.50
#Mann=6,-1,0
  4753.4    0.16       0  4783.5    0.07       0  4995.1    0.07       0
  4999.1    0.07       0  5199.8    0.16       0  5238.2    0.07       0
Bank Sta=4995.1,4999.1
Exp/Cntr=0.3,0.1

Type RM Length L Ch R = 1,1022,226,226,226
BEGIN DESCRIPTION:
462
END DESCRIPTION:
XS GIS Cut Line= 3
      1531555.01      6772238.03      1531457.48      6771943.88
      1531154.99      6771688.00
#Sta/Elev= 30
  4690.1 2082.93  4732.3 2069.37  4774.6 2051.10  4827.1 2038.97  4835.2 2034.08
  4848.2 2031.01  4864.4 2032.57  4896.1 2022.49  4951.5 2018.85  4951.8 2018.35
  4955.5 2018.85  5057.7 2020.30  5105.6 2021.07  5140.7 2028.77  5155.0 2026.80
  5197.9 2039.58  5274.1 2050.43  5296.8 2056.65  5304.5 2054.17  5311.0 2059.04
  5316.5 2056.23  5325.3 2052.29  5331.9 2059.83  5339.6 2058.63  5346.2 2066.93
  5353.9 2067.07  5360.5 2073.45  5368.2 2073.53  5389.0 2083.91  5396.2 2083.64
#Mann=7,-1,0
  4690.1    0.07       0  4835.2    0.16       0  4951.5    0.07       0
  4955.5    0.16       0  5057.7    0.07       0  5274.1    0.16       0
  5316.5    0.07       0
Bank Sta=4951.5,4955.5
Exp/Cntr=0.3,0.1

Type RM Length L Ch R = 1,796,604,604,604
BEGIN DESCRIPTION:
800
END DESCRIPTION:
XS GIS Cut Line= 3
      1531797.43      6772183.08      1531603.50      6771790.32
      1531323.67      6771613.58
#Sta/Elev= 30
  4557.1 2068.65  4593.6 2056.81  4607.4 2056.56  4621.6 2050.57  4638.5 2052.57
  4644.0 2047.88  4660.9 2044.90  4683.3 2033.26  4696.6 2030.96  4711.4 2034.02
  4728.2 2028.41  4733.8 2029.42  4750.7 2025.55  4756.3 2028.66  4773.1 2024.64
  4818.0 2025.08  4830.4 2021.87  4865.0 2020.00  5008.0 2016.75  5008.2 2016.25
  5012.0 2016.75  5082.9 2016.94  5153.3 2024.52  5213.5 2036.22  5234.7 2043.37
  5250.0 2043.71  5256.0 2046.65  5265.2 2048.73  5313.5 2070.88  5326.1 2072.47
#Mann=6,-1,0
  4557.1    0.07       0  4865.0    0.16       0  5008.0    0.07       0
  5012.0    0.16       0  5153.3    0.07       0  5256.0    0.16       0
Bank Sta=5008,5012
Exp/Cntr=0.3,0.1

Type RM Length L Ch R = 1,192,0,0,0
BEGIN DESCRIPTION:
461
END DESCRIPTION:
XS GIS Cut Line= 3
      1531934.89      6772207.59      1532031.59      6771460.43
      1531515.13      6771402.48
#Sta/Elev= 30
  4246.6 2055.64  4256.3 2053.89  4289.0 2053.84  4316.8 2046.03  4368.3 2040.95
  4387.4 2034.29  4457.9 2032.45  4488.2 2034.61  4516.8 2025.45  4538.6 2022.16
  4578.9 2022.48  4609.2 2031.18  4619.3 2030.98  4629.4 2026.80  4649.5 2014.42
  4669.7 2010.57  4793.9 2010.00  4975.6 2009.12  4980.3 2009.00  4980.5 2008.50
  4984.3 2009.00  4991.8 2009.12  5028.1 2009.32  5107.9 2009.18  5308.5 2011.38
  5379.0 2027.47  5419.2 2039.88  5429.8 2045.72  5449.4 2051.02  5519.7 2059.61
#Mann=8,-1,0
  4246.6    0.07       0  4793.9    0.12       0  4975.6    0.07       0
  4980.3    0.07       0  4984.3    0.07       0  4991.8    0.12       0
  5028.1    0.07       0  5107.9    0.16       0
Bank Sta=4980.3,4984.3
Exp/Cntr=0.3,0.1

Chan Stop Cuts=-1