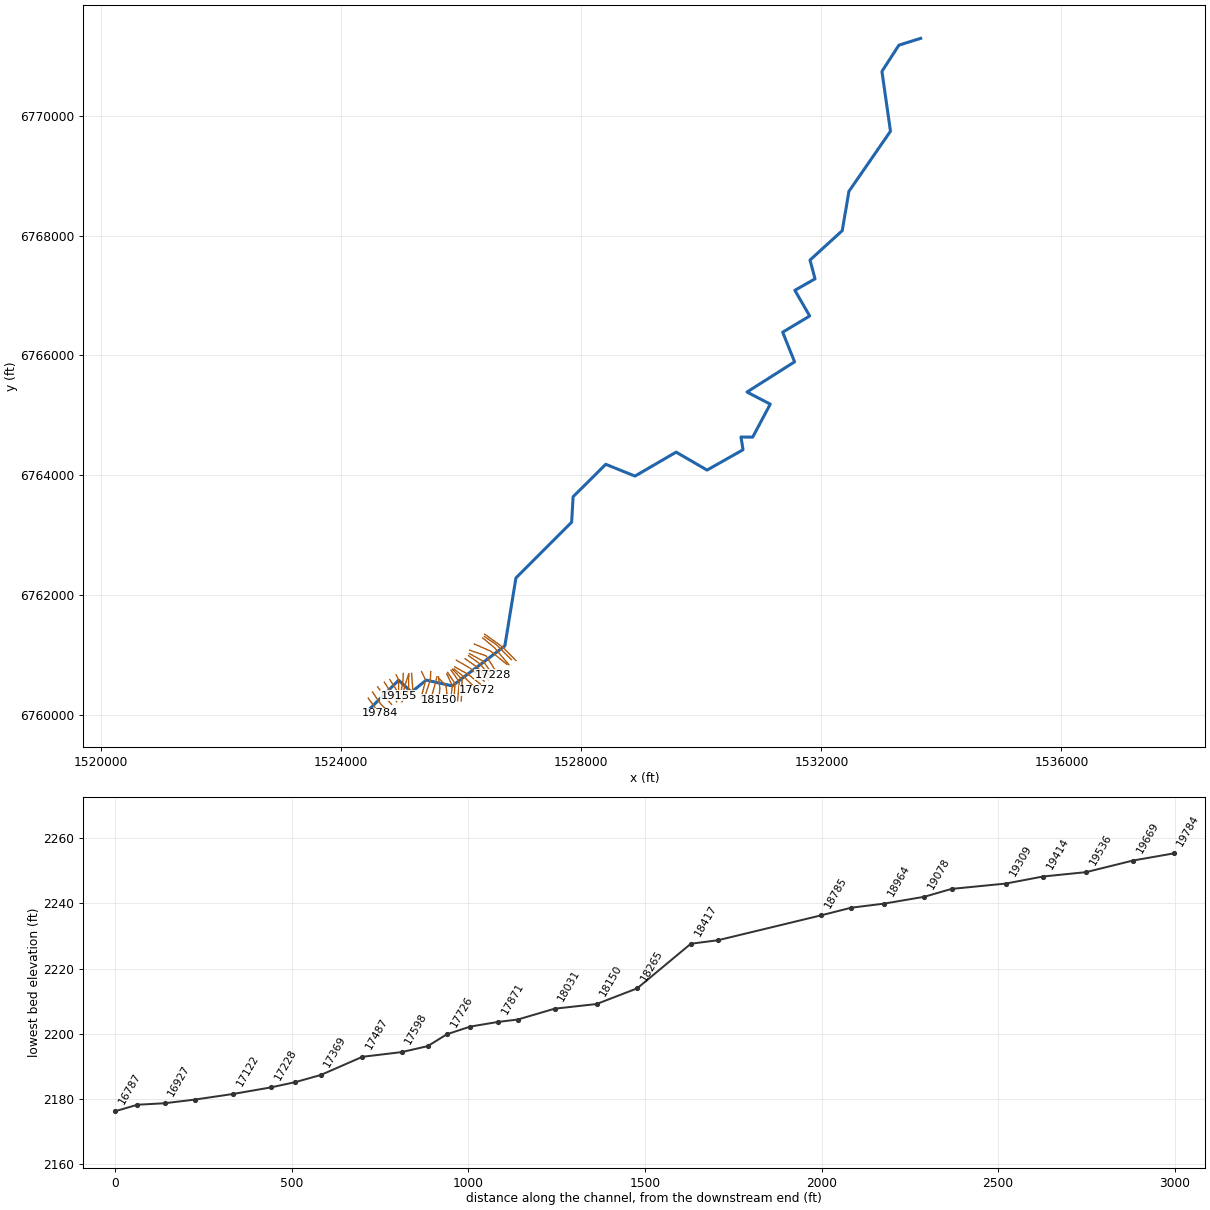
--- Elm 74.prj (project) ---

Proj Title=Elm 74 Base Level Engineering
Current Plan=p01
Default Exp/Contr=0.3,0.1
English Units
Geom File=g01
Flow File=f01
Plan File=p01
Y Axis Title=Elevation
X Axis Title(PF)=Main Channel Distance
X Axis Title(XS)=Station
BEGIN DESCRIPTION:
Elm 74
END DESCRIPTION:
DSS Export Rating Curves= 0
DSS Export Rating Curve Sorted= 0
DSS Export Volume Flow Curves= 0
DXF OffsetX= 0
DXF OffsetY= 0
DXF ScaleX= 1
DXF ScaleY= 10

--- Elm 74.p01 (plan) ---

Plan Title=Multiple Run
Short Identifier=Multiple
Geom File=g01
Flow File=f01
Subcritical Flow
K Sum by GR= 0
Std Step Tol= 0.01
Critical Tol= 0.01
Num of Std Step Trials= 20
Max Error Tol= 0.3
Flow Tol Ratio= 0.001
Split Flow NTrial= 30
Split Flow Tol= 0.02
Split Flow Ratio= 0.02
Log Output Level= 0
Friction Slope Method= 1
Unsteady Friction Slope Method= 2
Unsteady Bridges Friction Slope Method= 1
Parabolic Critical Depth
Global Vel Dist=  1 , 1 , 1
Global Log Level= 0
CheckData=True
Encroach Param= -1, 0, 0, 0
BEGIN DESCRIPTION:
Multiple Run
END DESCRIPTION:

--- Elm 74.f01 (steady flow) ---

Flow Title=Multiple
Number of Profiles=7
Profile Names=10-year,25-year,50-year,1pct_min,100-year,1pct_plu,500-year
River Rch & RM= Elm 74,Reach-1,19784
     351     505     639     502     804    1110    1290
River Rch & RM= Elm 74,Reach-1,13957
     418     605     767     603     967    1330    1560
River Rch & RM= Elm 74,Reach-1,9437
     699    1040    1340    1070    1720    2360    2860
River Rch & RM= Elm 74,Reach-1,6663
     686    1010    1300    1030    1660    2280    2730
Boundary for River Rch & Prof#=Elm 74,Reach-1,1
Up Type=0
Dn Type=3
Dn Slope=0.005
Boundary for River Rch & Prof#=Elm 74,Reach-1,2
Up Type=0
Dn Type=3
Dn Slope=0.005
Boundary for River Rch & Prof#=Elm 74,Reach-1,3
Up Type=0
Dn Type=3
Dn Slope=0.005
Boundary for River Rch & Prof#=Elm 74,Reach-1,4
Up Type=0
Dn Type=3
Dn Slope=0.005
Boundary for River Rch & Prof#=Elm 74,Reach-1,5
Up Type=0
Dn Type=3
Dn Slope=0.005
Boundary for River Rch & Prof#=Elm 74,Reach-1,6
Up Type=0
Dn Type=3
Dn Slope=0.005
Boundary for River Rch & Prof#=Elm 74,Reach-1,7
Up Type=0
Dn Type=3
Dn Slope=0.005

--- Elm 74.g01 (geometry) ---

Geom Title=Existing Conditions
Program Version=4.10

River Reach=Elm 74          ,Reach-1
Reach XY= 30
        1524455.        6760088.      1524956.33      6760584.68
      1525170.36      6760387.89      1525415.45      6760586.97
      1525849.07      6760490.25      1526725.65       6761157.4
      1526910.46      6762290.45      1527838.55      6763220.86
      1527862.69      6763644.47      1528406.63      6764184.88
      1528894.46      6763989.08      1529580.03      6764388.51
      1530094.67      6764088.87      1530694.03      6764427.62
      1530660.45      6764641.01        1530855.        6764638.
      1531148.03      6765188.25      1530760.05      6765390.28
      1531553.46      6765893.85        1531355.        6766388.
       1531805.4      6766658.13      1531557.99      6767086.54
      1531894.22       6767277.8      1531810.36       6767590.7
      1532347.51      6768081.31      1532458.83      6768736.42
      1533151.46      6769739.46      1533008.75      6770736.45
      1533291.69       6771174.6        1533655.        6771288.

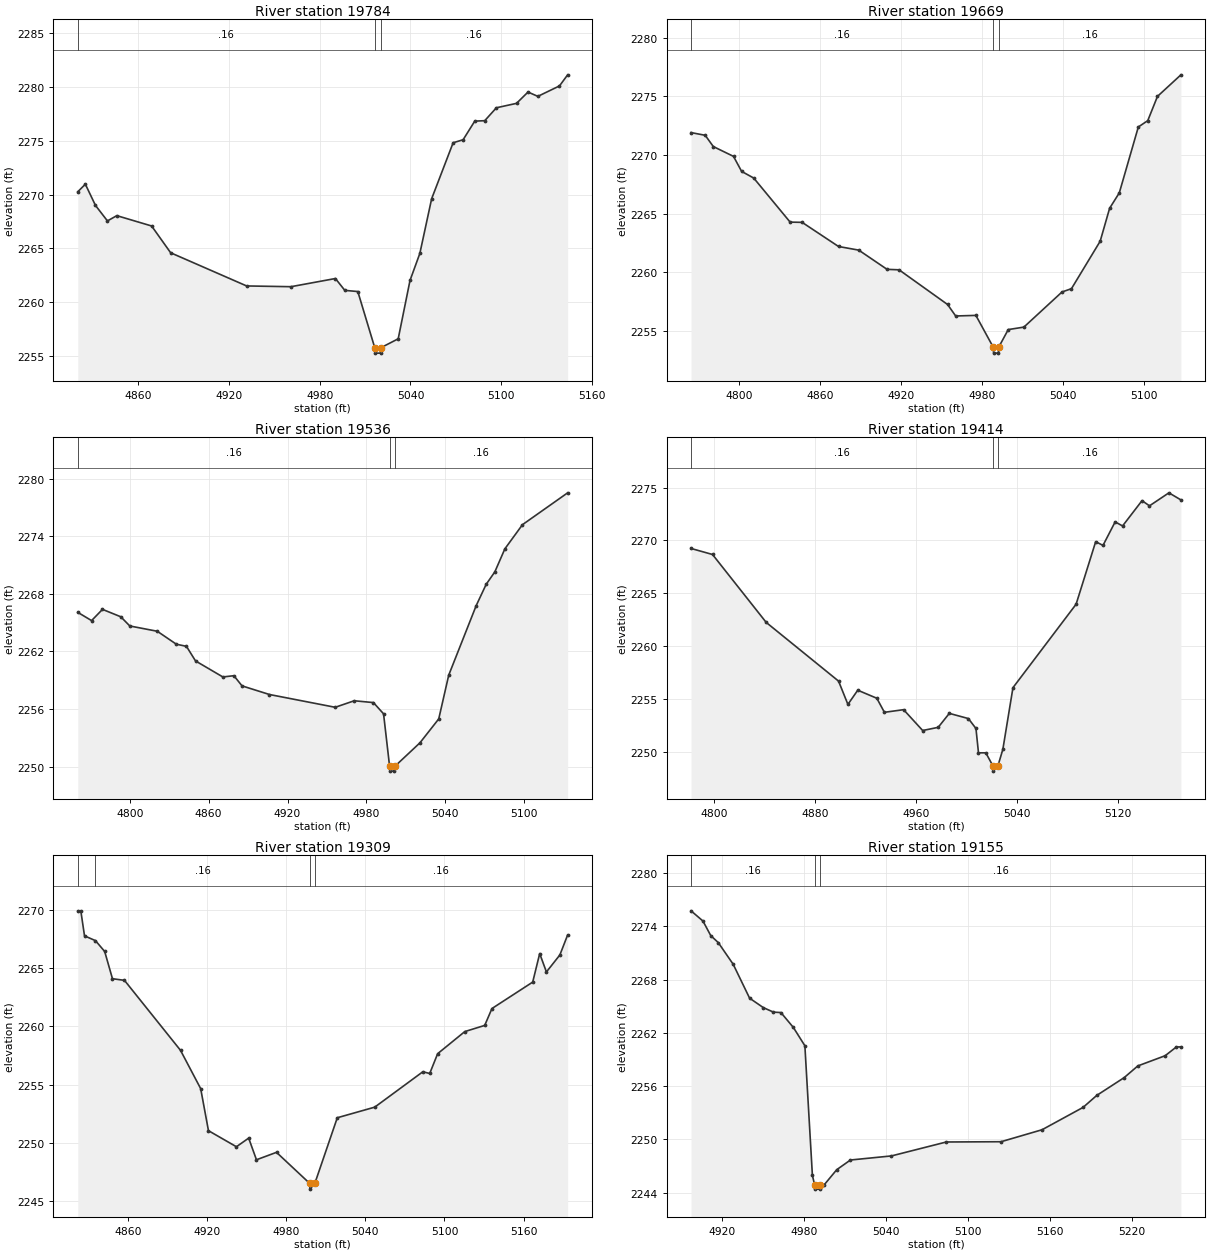
Type RM Length L Ch R = 1 ,19784   ,115,115,115
BEGIN DESCRIPTION:
Elm 74 4328
END DESCRIPTION:
XS GIS Cut Line= 3
      1524447.39      6760287.45      1524553.33      6760142.04
      1524646.32      6760032.23
#Sta/Elev= 30
  4820.1 2270.26  4825.1 2270.96  4831.8 2268.99  4839.7 2267.55  4845.9 2268.04
  4868.9 2267.08  4881.5 2264.59  4931.7 2261.51    4961 2261.44  4990.4  2262.2
  4996.6  2261.1  5005.2 2260.99  5016.4 2255.77  5016.7 2255.27  5020.2 2255.27
  5020.4 2255.77  5031.9  2256.6  5039.7 2262.02  5046.2 2264.53    5054 2269.61
  5068.2 2274.81  5074.8 2275.09  5082.5 2276.82  5089.1 2276.86  5096.8 2278.06
  5110.1 2278.47  5117.7 2279.52  5124.2 2279.12  5138.5 2280.09  5143.9 2281.12
#Mann= 3 ,-1 , 0
  4820.1     .16       0  5016.4     .07       0  5020.4     .16       0
Bank Sta=5016.4,5020.4
XS Rating Curve= 0 ,0
Exp/Cntr=0.3,0.1

Type RM Length L Ch R = 1 ,19669   ,133,133,133
BEGIN DESCRIPTION:
Elm 74 4326
END DESCRIPTION:
XS GIS Cut Line= 3
      1524521.15      6760387.31      1524653.37      6760191.95
      1524744.71      6760102.99
#Sta/Elev= 30
  4764.1 2271.91  4774.6 2271.68  4780.6 2270.72  4795.6 2269.88  4801.6  2268.6
  4810.6 2268.03  4837.6 2264.27  4846.5 2264.25  4873.5 2262.19  4888.5 2261.88
  4909.5 2260.24  4918.4  2260.2  4954.4 2257.24  4960.4 2256.26  4975.4 2256.31
  4988.3 2253.59  4988.6 2253.09  4992.1 2253.09  4992.3 2253.59  4999.4  2255.1
    5011 2255.31  5039.3 2258.31  5046.3 2258.59  5067.6 2262.64  5074.6 2265.45
  5081.8 2266.77  5095.9 2272.39  5102.9 2272.93  5110.1    2275  5127.5 2276.84
#Mann= 3 ,-1 , 0
  4764.1     .16       0  4988.3     .07       0  4992.3     .16       0
Bank Sta=4988.3,4992.3
XS Rating Curve= 0 ,0
Exp/Cntr=0.3,0.1

Type RM Length L Ch R = 1 ,19536   ,122,122,122
BEGIN DESCRIPTION:
Elm 74 4325
END DESCRIPTION:
XS GIS Cut Line= 3
      1524605.79      6760474.12      1524749.63       6760282.5
      1524837.16       6760182.1
#Sta/Elev= 30
  4760.4 2266.07  4770.9 2265.21  4779.2 2266.38  4793.1 2265.61    4800 2264.65
  4820.9  2264.1  4835.4 2262.75  4843.1 2262.53    4850 2261.01  4870.8 2259.34
  4879.2 2259.47  4885.4 2258.41  4906.3 2257.51  4956.3 2256.18  4970.8 2256.86
  4985.4 2256.67  4993.1  2255.5  4997.7 2250.03  4997.9 2249.53  5001.4 2249.53
  5001.7 2250.03  5020.8 2252.48  5035.1 2254.97  5042.7 2259.53  5063.6 2266.77
  5071.2 2268.99  5077.8 2270.29  5085.4 2272.68  5098.8  2275.2  5133.2 2278.52
#Mann= 3 ,-1 , 0
  4760.4     .16       0  4997.7     .07       0  5001.7     .16       0
Bank Sta=4997.7,5001.7
XS Rating Curve= 0 ,0
Exp/Cntr=0.3,0.1

Type RM Length L Ch R = 1 ,19414   ,105,105,105
BEGIN DESCRIPTION:
Elm 74 19406.227
END DESCRIPTION:
XS GIS Cut Line= 3
      1524717.26      6760552.28      1524842.08      6760359.62
      1524924.78      6760224.59
#Sta/Elev= 30
  4781.9 2269.24  4798.9 2268.67  4841.4 2262.25  4898.7  2256.7  4906.1  2254.5
  4913.9 2255.84    4929 2255.08    4935 2253.75  4950.2    2254  4965.3 2252.03
  4977.6 2252.33  4986.4 2253.65  5001.5 2253.16  5007.5 2252.22  5009.5 2249.92
  5015.3 2249.92  5020.9 2248.69  5021.2 2248.19  5024.9 2248.69  5028.8 2250.25
  5036.8 2256.08  5086.8 2263.97  5102.3 2269.88  5108.1 2269.53  5117.7 2271.75
  5123.6 2271.37    5139 2273.76  5144.9 2273.27  5160.3  2274.5  5169.8 2273.83
#Mann= 3 ,-1 , 0
  4781.9     .16       0  5020.9     .07       0  5024.9     .16       0
Bank Sta=5020.9,5024.9
XS Rating Curve= 0 ,0
Exp/Cntr=0.3,0.1

Type RM Length L Ch R = 1 ,19309   ,154,154,154
BEGIN DESCRIPTION:
Elm 74 19309.29
END DESCRIPTION:
XS GIS Cut Line= 3
      1524807.59      6760597.85      1524913.95      6760430.71
      1524954.98      6760262.25
#Sta/Elev= 30
  4821.9 2269.93  4824.2 2269.93    4827 2267.78  4835.3 2267.37  4842.3 2266.44
  4848.2  2264.1  4857.3 2263.96  4899.8 2257.95  4915.1 2254.66    4921 2251.05
  4942.2 2249.67  4951.5 2250.41  4957.4 2248.55  4972.6 2249.19  4997.7 2246.53
    4998 2246.03  5001.7 2246.53  5018.7 2252.16  5047.1 2253.07  5083.6 2256.11
  5088.8 2255.96  5094.8 2257.66  5115.4 2259.56  5130.5 2260.09    5136 2261.54
  5166.9 2263.81  5172.2 2266.26  5177.3 2264.68  5187.5 2266.14  5193.4 2267.86
#Mann= 4 ,-1 , 0
  4821.9     .07       0  4835.3     .16       0  4997.7     .07       0
  5001.7     .16       0
Bank Sta=4997.7,5001.7
XS Rating Curve= 0 ,0
Exp/Cntr=0.3,0.1

Type RM Length L Ch R = 1 ,19155   ,77,77,77
BEGIN DESCRIPTION:
Elm 74 19155.39
END DESCRIPTION:
XS GIS Cut Line= 3
      1524913.95      6760675.94      1524953.01       6760591.3
      1524959.52       6760326.5
#Sta/Elev= 30
  4897.7 2275.74  4906.4 2274.59  4912.1 2272.95  4917.6 2272.16  4928.5 2269.72
  4940.5  2265.9  4950.5 2264.84  4957.9 2264.33  4963.4 2264.28  4972.5  2262.6
  4980.9 2260.54  4986.4 2245.94    4988 2244.89  4988.2 2244.39  4991.7 2244.39
    4992 2244.89  4995.1 2244.89  5004.2 2246.58  5014.2 2247.67  5044.2 2248.13
  5084.3  2249.7  5124.3 2249.73  5154.3 2251.08  5184.3  2253.6  5194.3 2254.95
  5214.3 2256.95  5224.3 2258.27  5244.3 2259.42  5252.5 2260.41  5255.8 2260.41
#Mann= 3 ,-1 , 0
  4897.7     .16       0    4988     .07       0    4992     .16       0
Bank Sta=4988,4992
XS Rating Curve= 0 ,0
Exp/Cntr=0.3,0.1

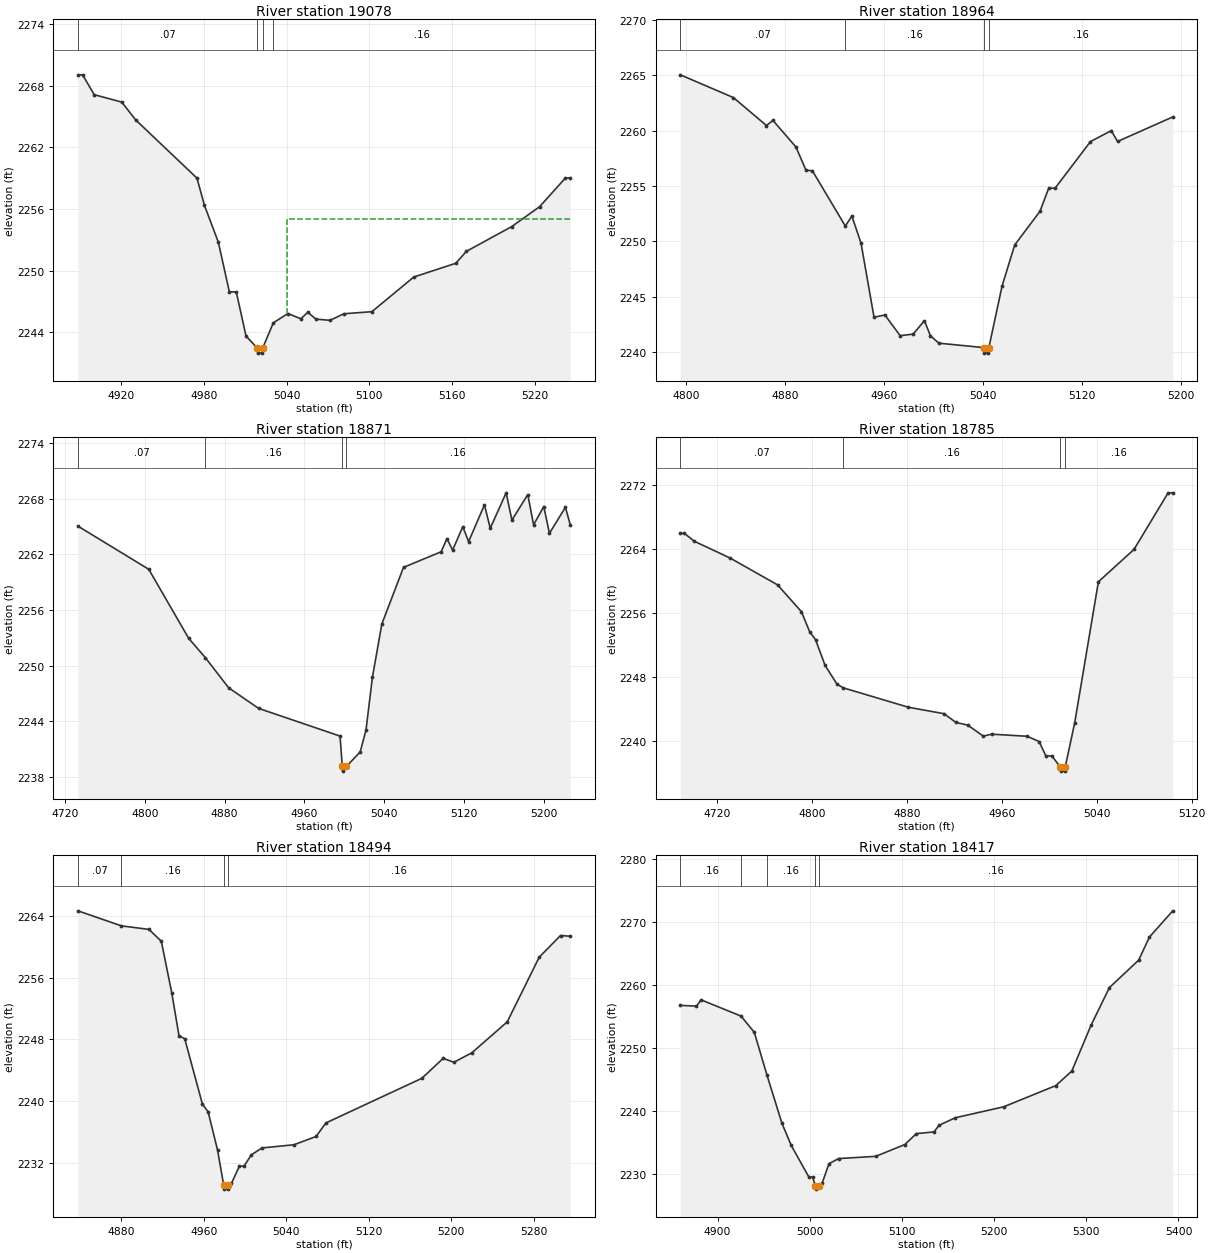
Type RM Length L Ch R = 1 ,19078   ,114,114,114
BEGIN DESCRIPTION:
Elm 74 19078.37
END DESCRIPTION:
XS GIS Cut Line= 3
       1525033.3      6760699.78      1525028.96      6760586.96
      1524987.73      6760346.06
#Sta/Elev= 30
  4888.5 2269.05  4891.9 2269.05  4900.3 2267.12  4920.3  2266.4  4930.3 2264.68
  4974.9    2259  4980.3 2256.36  4990.4 2252.77  4998.4 2247.94  5003.4 2247.94
  5010.5 2243.64  5018.6 2242.48  5018.9 2241.98  5022.4 2241.98  5022.6 2242.48
  5030.3 2244.93  5040.9 2245.83  5050.3 2245.32  5055.3 2245.95  5061.2 2245.29
  5071.4 2245.17  5081.5 2245.81  5101.8 2246.01  5132.2 2249.38  5162.7 2250.72
  5170.4 2251.88  5203.3 2254.29  5223.5 2256.22  5242.3 2259.02  5245.8 2259.02
#Mann= 4 ,-1 , 0
  4888.5     .07       0  5018.6     .07       0  5022.6     .07       0
  5030.3     .16       0
#XS Ineff= 2 , 0
       0                    5040       0    2255
Permanent Ineff=
       F       F
Bank Sta=5018.6,5022.6
XS Rating Curve= 0 ,0
Exp/Cntr=0.3,0.1

Type RM Length L Ch R = 1 ,18964   ,93,93,93
BEGIN DESCRIPTION:
Elm 74 18964.3
END DESCRIPTION:
XS GIS Cut Line= 3
       1525122.3      6760686.84      1525059.35      6760493.65
      1525020.33      6760302.88
#Sta/Elev= 30
  4795.2 2265.06  4838.1    2263  4864.8 2260.47    4870 2260.94  4888.6 2258.53
  4896.7 2256.43  4901.9 2256.38  4928.5 2251.38  4933.8 2252.28  4941.2 2249.83
  4951.7 2243.13  4960.5 2243.33  4972.8 2241.46  4983.3  2241.6  4992.4 2242.81
  4997.3 2241.45  5004.1 2240.78  5040.5 2240.38  5040.7 2239.88  5044.2 2239.88
  5044.5 2240.38  5055.2 2245.96  5065.4 2249.67  5085.8 2252.71  5092.9 2254.81
    5098  2254.8  5126.6 2259.02  5143.4 2260.01  5148.5 2259.03  5193.1 2261.25
#Mann= 4 ,-1 , 0
  4795.2     .07       0  4928.5     .16       0  5040.5     .07       0
  5044.5     .16       0
Bank Sta=5040.5,5044.5
XS Rating Curve= 0 ,0
Exp/Cntr=0.3,0.1

Type RM Length L Ch R = 1 ,18871   ,86,86,86
BEGIN DESCRIPTION:
Elm 74 18870.8
END DESCRIPTION:
XS GIS Cut Line= 3
      1525124.45      6760688.97      1525122.28      6760426.37
      1525009.69      6760225.01
#Sta/Elev= 30
    4733 2265.06    4804  2260.4    4844 2252.95  4860.7 2250.87    4884 2247.62
    4914  2245.4  4995.6 2242.41  4997.9 2239.13  4998.1 2238.63  5001.9 2239.13
  5015.8  2240.7  5021.6 2243.05  5028.1 2248.79  5037.5  2254.5  5059.2 2260.61
  5096.9 2262.29  5102.7 2263.71  5108.4 2262.47  5118.6    2265  5124.4 2263.39
  5140.3 2267.35  5146.1 2264.82    5162 2268.65  5167.8 2265.71  5183.7 2268.46
  5189.5  2265.2  5199.7 2267.17  5205.4 2264.28  5221.4 2267.09  5226.3 2265.19
#Mann= 4 ,-1 , 0
    4733     .07       0  4860.7     .16       0  4997.9     .07       0
  5001.9     .16       0
Bank Sta=4997.9,5001.9
XS Rating Curve= 0 ,0
Exp/Cntr=0.3,0.1

Type RM Length L Ch R = 1 ,18785   ,291,291,291
BEGIN DESCRIPTION:
Elm 74 18784.75
END DESCRIPTION:
XS GIS Cut Line= 3
      1525172.19      6760699.81       1525193.9      6760391.65
       1525193.9      6760285.28
#Sta/Elev= 30
  4688.7    2266  4692.1    2266  4700.5 2265.01  4730.6 2262.92  4770.7 2259.56
  4790.8 2256.21  4797.8 2253.69  4802.8 2252.68  4810.8 2249.48  4820.8 2247.15
    4826 2246.69    4881 2244.26  4911.1 2243.45  4921.1 2242.36  4931.1 2242.02
  4944.2 2240.65  4951.2 2240.89  4981.2 2240.63  4991.3 2239.97    4997 2238.17
    5002 2238.17  5009.3 2236.77  5009.5 2236.27    5013 2236.27  5013.3 2236.77
  5021.3 2242.32  5041.3 2259.95  5071.3 2263.99  5100.1 2271.07    5104 2271.07
#Mann= 4 ,-1 , 0
  4688.7     .07       0    4826     .16       0  5009.3     .07       0
  5013.3     .16       0
Bank Sta=5009.3,5013.3
XS Rating Curve= 0 ,0
Exp/Cntr=0.3,0.1

Type RM Length L Ch R = 1 ,18494   ,77,77,77
BEGIN DESCRIPTION:
Elm 74 18494.42
END DESCRIPTION:
XS GIS Cut Line= 3
      1525337.13      6760730.18      1525406.57      6760584.79
      1525326.26      6760278.77
#Sta/Elev= 30
  4837.9 2264.62    4880 2262.68  4906.8 2262.22  4918.8 2260.69    4929 2253.96
  4935.9  2248.5  4941.5 2248.09  4958.6 2239.67  4964.2 2238.64  4973.3 2233.73
  4979.3 2229.17  4979.6 2228.67  4983.1 2228.67  4983.3 2229.17  4986.8 2229.41
  4994.5 2231.64    4999 2231.64    5006 2233.09  5016.4 2233.99  5047.4  2234.4
  5068.8 2235.47  5078.4 2237.22  5171.5 2242.99  5192.1 2245.56  5202.5 2245.06
  5219.9 2246.28  5254.2 2250.27  5285.2 2258.62  5305.9 2261.43  5315.4 2261.34
#Mann= 4 ,-1 , 0
  4837.9     .07       0    4880     .16       0  4979.3     .07       0
  4983.3     .16       0
Bank Sta=4979.3,4983.3
XS Rating Curve= 0 ,0
Exp/Cntr=0.3,0.1

Type RM Length L Ch R = 1 ,18417   ,152,152,152
BEGIN DESCRIPTION:
Elm 74 18417.49
END DESCRIPTION:
XS GIS Cut Line= 3
       1525491.2      6760728.03      1525482.52      6760584.79
      1525359.65      6760214.02
#Sta/Elev= 30
  4859.7  2256.8  4877.2 2256.68  4882.2 2257.68  4925.5  2255.1  4939.9 2252.52
  4953.7  2245.7  4969.9 2238.05    4980 2234.53  4999.1 2229.51  5003.2 2229.51
  5006.2 2228.09  5006.4 2227.59  5010.2 2228.09  5013.4  2228.5  5020.9 2231.63
  5031.4 2232.45  5071.6  2232.8  5103.2 2234.68  5115.7 2236.41  5134.9 2236.69
  5140.2 2237.73  5157.8 2238.93  5210.5 2240.68    5267 2244.05  5284.3 2246.36
  5305.3 2253.68  5325.1 2259.63  5356.8 2263.99  5368.5 2267.66  5393.8 2271.83
#Mann= 5 ,-1 , 0
  4859.7     .16       0  4925.5     .07       0  4953.7     .16       0
  5006.2     .07       0  5010.2     .16       0
Bank Sta=5006.2,5010.2
XS Rating Curve= 0 ,0
Exp/Cntr=0.3,0.1

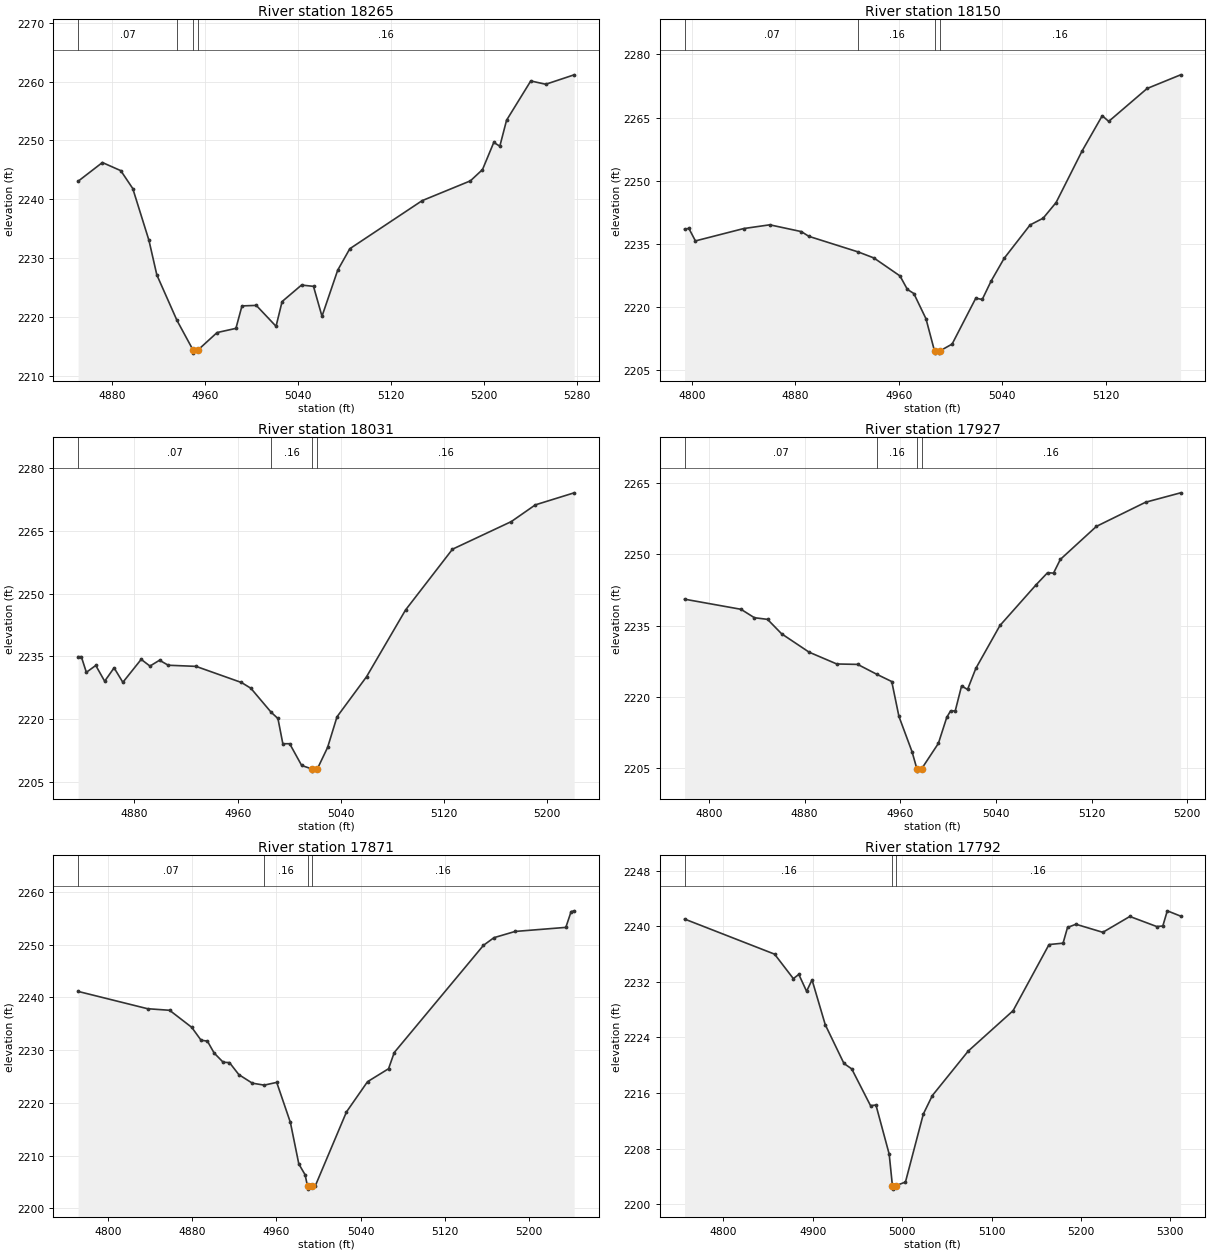
Type RM Length L Ch R = 1 ,18265   ,115,115,115
BEGIN DESCRIPTION:
Elm 74 18265.23
END DESCRIPTION:
XS GIS Cut Line= 3
      1525595.37       6760643.4      1525556.31      6760497.99
      1525482.79      6760232.03
#Sta/Elev= 30
    4851 2243.08  4871.9 2246.26  4887.7 2244.88    4898 2241.85  4911.9 2233.07
  4918.7 2227.19    4936 2219.48  4949.9 2214.42  4950.1 2213.92  4953.9 2214.42
  4970.5 2217.41  4986.7 2218.12  4991.9 2221.93  5004.2 2222.02  5021.2 2218.47
  5026.4 2222.67  5043.1 2225.47  5053.4 2225.25  5060.7 2220.17  5074.2 2227.99
  5084.6 2231.63  5146.8 2239.79  5188.3 2243.15  5198.7 2245.06  5208.4 2249.67
  5213.6 2249.03  5219.4 2253.44  5240.2  2260.1  5253.1 2259.54  5277.5 2261.14
#Mann= 4 ,-1 , 0
    4851     .07       0    4936     .16       0  4949.9     .07       0
  4953.9     .16       0
Bank Sta=4949.9,4953.9
XS Rating Curve= 0 ,0
Exp/Cntr=0.3,0.1

Type RM Length L Ch R = 1 ,18150   ,119,119,119
BEGIN DESCRIPTION:
Elm 74 18150.08
END DESCRIPTION:
XS GIS Cut Line= 3
      1525619.24      6760643.38      1525643.11       6760445.9
      1525623.67      6760262.24
#Sta/Elev= 30
  4794.3 2238.49  4797.6 2238.71  4802.7 2235.73    4840 2238.66  4860.2 2239.55
  4884.6 2237.94  4890.4 2236.82  4928.8 2233.09  4940.7 2231.69  4960.9 2227.42
  4966.6 2224.23  4971.6 2223.25    4981 2217.26  4987.6 2209.61  4987.9 2209.11
  4991.4 2209.11  4991.6 2209.61  5001.2 2211.26  5019.5 2222.14  5024.5 2221.84
  5031.3 2226.17  5041.4 2231.58  5061.5 2239.52  5071.6 2241.12  5081.6 2244.83
  5101.7 2257.06  5117.3 2265.43  5122.3 2264.08    5152 2271.89  5177.9 2275.13
#Mann= 4 ,-1 , 0
  4794.3     .07       0  4928.8     .16       0  4987.6     .07       0
  4991.6     .16       0
Bank Sta=4987.6,4991.6
XS Rating Curve= 0 ,0
Exp/Cntr=0.3,0.1

Type RM Length L Ch R = 1 ,18031   ,104,104,104
BEGIN DESCRIPTION:
Elm 74 18031.25
END DESCRIPTION:
XS GIS Cut Line= 4
      1525636.59      6760608.68      1525745.11      6760491.48
      1525764.64      6760320.04      1525768.98        6760268.
#Sta/Elev= 30
  4836.3 2234.95  4838.8 2234.95  4842.7 2231.22    4850 2232.86  4856.9  2229.1
  4864.2 2232.29    4871 2228.84  4885.2 2234.31    4892 2232.71  4899.4  2234.1
  4906.2 2232.91  4927.7 2232.64  4962.9  2228.8  4970.2 2227.43  4985.9 2221.72
  4991.2 2220.22    4995 2214.21  5000.3 2214.21  5009.6 2209.03  5017.7 2208.18
  5017.9 2207.68  5021.7 2208.18  5029.7 2213.33    5037 2220.63  5059.9 2230.18
  5090.1 2246.07  5126.5 2260.56  5172.1 2267.14  5190.7 2271.12  5220.8 2273.99
#Mann= 4 ,-1 , 0
  4836.3     .07       0  4985.9     .16       0  5017.7     .07       0
  5021.7     .16       0
Bank Sta=5017.7,5021.7
XS Rating Curve= 0 ,0
Exp/Cntr=0.3,0.1

Type RM Length L Ch R = 1 ,17927   ,56,56,56
BEGIN DESCRIPTION:
Elm 74 17926.84
END DESCRIPTION:
XS GIS Cut Line= 3
      1525758.15      6760691.09      1525851.45      6760487.14
       1525825.4       6760298.3
#Sta/Elev= 30
  4779.6 2240.56  4826.8 2238.43    4838 2236.66    4849 2236.31  4860.8 2233.27
  4883.8  2229.4  4906.9 2226.92  4924.4 2226.83  4940.6 2224.72  4952.9 2223.22
  4958.9 2215.88  4969.9 2208.42  4973.9 2204.86  4974.2 2204.36  4977.9 2204.86
  4991.9  2210.2  4998.9 2215.68  5002.1 2217.04    5006 2217.04  5011.3  2222.3
  5016.3 2221.55  5023.2 2225.98  5043.4 2235.02  5073.7 2243.61  5083.2 2246.13
  5088.2 2246.05  5093.9 2248.93  5124.1 2255.89  5165.2 2260.97  5194.5 2262.95
#Mann= 4 ,-1 , 0
  4779.6     .07       0  4940.6     .16       0  4973.9     .07       0
  4977.9     .16       0
Bank Sta=4973.9,4977.9
XS Rating Curve= 0 ,0
Exp/Cntr=0.3,0.1

Type RM Length L Ch R = 1 ,17871   ,79,79,79
BEGIN DESCRIPTION:
Elm 74 17870.64
END DESCRIPTION:
XS GIS Cut Line= 3
      1525771.16        6760715.      1525894.85      6760532.71
      1525879.72      6760281.96
#Sta/Elev= 30
  4771.5 2241.12  4837.5 2237.84  4858.5 2237.54  4879.5 2234.31  4888.4 2231.86
  4894.4  2231.7  4900.8 2229.44  4909.4 2227.69  4915.4 2227.62  4924.3 2225.34
  4937.1 2223.72  4948.4 2223.35  4960.3 2223.87  4973.3 2216.27  4981.3  2208.4
  4987.3 2206.34  4989.6 2204.13  4989.9 2203.63  4993.6 2204.13  4996.7 2204.13
  5026.6 2218.27  5046.6    2224  5066.6 2226.46    5072 2229.53  5156.8 2249.86
  5166.8 2251.31  5186.9 2252.49  5235.1 2253.26  5240.1 2256.25    5243  2256.4
#Mann= 4 ,-1 , 0
  4771.5     .07       0  4948.4     .16       0  4989.6     .07       0
  4993.6     .16       0
Bank Sta=4989.6,4993.6
XS Rating Curve= 0 ,0
Exp/Cntr=0.3,0.1

Type RM Length L Ch R = 1 ,17792   ,66,66,66
BEGIN DESCRIPTION:
Elm 74 17792.01
END DESCRIPTION:
XS GIS Cut Line= 3
      1525829.72      6760751.93      1525966.46      6760556.58
       1525938.4      6760241.38
#Sta/Elev= 30
  4756.5 2241.03  4857.2 2235.98  4878.2 2232.46  4884.3 2233.07    4893 2230.64
  4899.1 2232.28  4913.9 2225.83  4934.8 2220.26  4943.5 2219.48  4964.5  2214.2
  4970.6 2214.28  4985.4 2207.23    4989 2202.69  4989.3 2202.19    4993 2202.69
  5003.6 2203.21  5023.6 2212.99  5033.7 2215.65  5073.8 2222.04    5124 2227.85
  5164.2 2237.36  5179.9 2237.56  5184.9 2239.82  5194.3 2240.28  5224.4 2239.12
  5254.6  2241.4  5284.7 2239.95  5291.5 2240.03  5296.5 2242.21  5311.4 2241.45
#Mann= 3 ,-1 , 0
  4756.5     .16       0    4989     .07       0    4993     .16       0
Bank Sta=4989,4993
XS Rating Curve= 0 ,0
Exp/Cntr=0.3,0.1

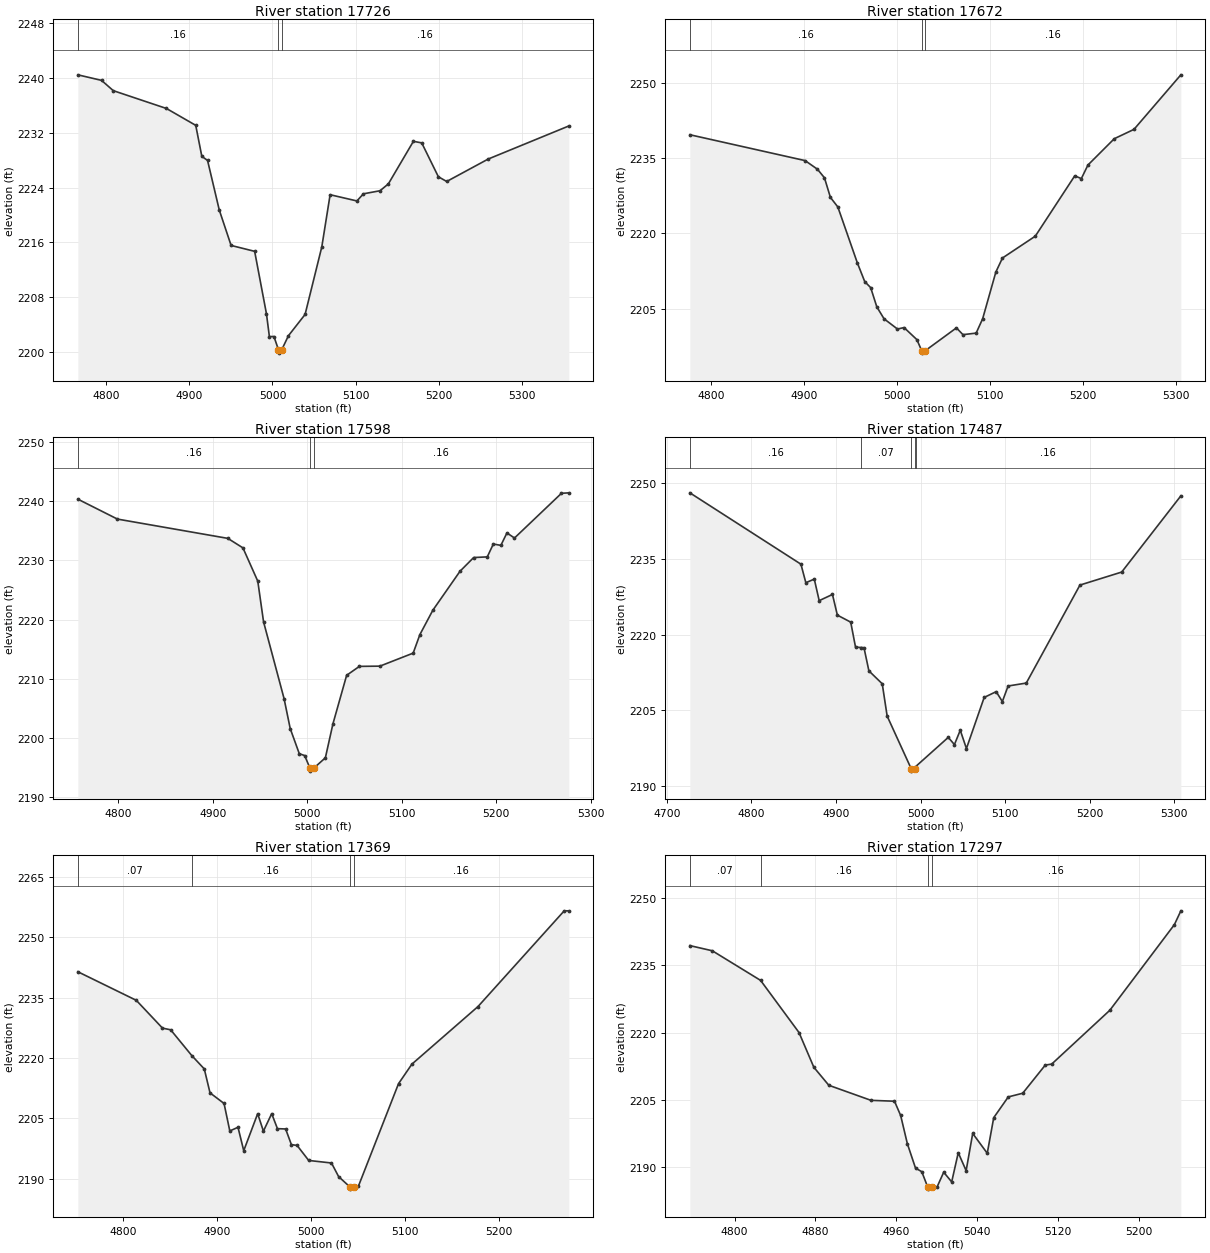
Type RM Length L Ch R = 1 ,17726   ,54,54,54
BEGIN DESCRIPTION:
Elm 74 17725.52
END DESCRIPTION:
XS GIS Cut Line= 3
      1525853.64      6760767.06      1526014.21      6760597.81
      1525999.08      6760241.33
#Sta/Elev= 30
  4766.1 2240.44  4794.6 2239.63  4808.7 2238.13  4872.6 2235.53  4907.8 2233.07
  4915.1 2228.55    4922 2227.95  4936.1 2220.71  4950.3 2215.55  4978.6 2214.69
  4992.8 2205.57  4996.3 2202.26  5001.8 2202.26  5007.2 2200.34  5007.5 2199.84
  5011.2 2200.34  5019.2 2202.38  5039.2 2205.48  5059.3 2215.34  5069.3 2222.95
  5101.5 2222.04  5109.3 2223.08  5129.3 2223.53  5139.3 2224.53  5169.4 2230.74
  5179.4 2230.51  5199.4 2225.57  5209.4 2224.88  5259.4 2228.16  5356.2 2232.98
#Mann= 3 ,-1 , 0
  4766.1     .16       0  5007.2     .07       0  5011.2     .16       0
Bank Sta=5007.2,5011.2
XS Rating Curve= 0 ,0
Exp/Cntr=0.3,0.1

Type RM Length L Ch R = 1 ,17672   ,74,74,74
BEGIN DESCRIPTION:
Elm 74 17671.89
END DESCRIPTION:
XS GIS Cut Line= 3
      1525877.48       6760773.6      1526055.44      6760632.54
      1526268.15      6760419.83
#Sta/Elev= 30
  4777.5 2239.62  4901.4 2234.48  4914.7 2232.76  4922.2 2231.06  4928.6 2227.17
  4936.6 2225.26  4957.5 2214.18  4965.5 2210.43  4971.9 2209.23  4978.5  2205.4
  4986.3 2203.03  5000.7    2201  5007.8 2201.29  5021.6 2198.89  5026.7 2196.71
  5026.9 2196.21  5030.7 2196.71  5064.1 2201.23  5071.1 2199.88  5085.3 2200.19
  5092.3 2203.05  5106.5 2212.34  5113.6 2215.12  5148.9 2219.46  5191.3 2231.45
  5198.4 2230.91  5205.5  2233.6  5233.8 2238.83    5255 2240.69  5305.4 2251.53
#Mann= 3 ,-1 , 0
  4777.5     .16       0  5026.7     .07       0  5030.7     .16       0
Bank Sta=5026.7,5030.7
XS Rating Curve= 0 ,0
Exp/Cntr=0.3,0.1

Type RM Length L Ch R = 1 ,17598   ,111,111,111
BEGIN DESCRIPTION:
Elm 74 17597.52
END DESCRIPTION:
XS GIS Cut Line= 3
      1525888.37       6760808.3      1526111.86      6760684.62
      1526318.06      6760519.66
#Sta/Elev= 30
  4757.3 2240.36  4799.2 2236.99    4916 2233.73    4932 2232.12  4947.7 2226.49
  4953.8 2219.62  4975.5 2206.64    4982 2201.58  4991.6 2197.33  4997.3 2197.01
  5002.9 2194.88  5003.1 2194.38  5006.9 2194.88  5019.2 2196.63  5027.2 2202.37
  5041.7 2210.58  5055.2 2212.09  5076.9 2212.13  5112.1 2214.33  5119.2 2217.46
  5132.9 2221.58  5161.7 2228.18  5176.1 2230.49  5190.5  2230.6  5196.9 2232.77
  5204.9 2232.55  5211.3 2234.65  5219.3 2233.79    5269 2241.35  5276.8 2241.43
#Mann= 3 ,-1 , 0
  4757.3     .16       0  5002.9     .07       0  5006.9     .16       0
Bank Sta=5002.9,5006.9
XS Rating Curve= 0 ,0
Exp/Cntr=0.3,0.1

Type RM Length L Ch R = 1 ,17487   ,118,118,118
BEGIN DESCRIPTION:
Elm 74 17486.72
END DESCRIPTION:
XS GIS Cut Line= 3
      1525916.59      6760918.97       1526153.1      6760782.28
      1526378.13      6760572.38
#Sta/Elev= 30
  4727.1 2248.12  4858.5 2233.97  4864.3  2230.3  4874.3 2231.01  4880.1 2226.74
  4895.8 2227.97  4901.6 2223.87  4917.4 2222.48  4923.1 2217.52  4929.7 2217.45
  4933.1 2217.41  4938.9 2212.82  4954.7 2210.26  4960.5 2203.86  4988.9 2193.44
  4989.2 2192.94  4992.9 2193.44  4994.2 2193.84  5032.8 2199.63  5040.1  2198.2
    5047 2201.05  5054.3 2197.42  5075.3 2207.55  5089.5  2208.7  5096.8 2206.73
  5103.6 2209.82  5125.1  2210.4  5188.6 2229.83    5238 2232.41    5308 2247.52
#Mann= 5 ,-1 , 0
  4727.1     .16       0  4929.7     .07       0  4988.9     .07       0
  4992.9     .07       0  4994.2     .16       0
Bank Sta=4988.9,4992.9
XS Rating Curve= 0 ,0
Exp/Cntr=0.3,0.1

Type RM Length L Ch R = 1 ,17369   ,72,72,72
BEGIN DESCRIPTION:
Elm 74 17368.62
END DESCRIPTION:
XS GIS Cut Line= 3
      1526064.08      6760942.89      1526265.94      6760801.81
      1526448.25      6760595.63
#Sta/Elev= 30
  4752.3 2241.42  4814.4 2234.31  4842.2  2227.4  4850.9 2226.98  4873.3 2220.58
  4886.6 2217.25  4892.7  2211.3  4907.6 2208.66  4913.7 2201.83  4922.4 2202.74
  4928.5 2196.92  4943.3 2206.12  4949.4 2201.78  4958.2 2206.13  4964.3  2202.4
    4973 2202.32  4979.1 2198.44  4985.2 2198.22  4997.5 2194.49  5021.7 2193.86
  5029.3 2190.47  5041.5 2187.86  5041.8 2187.36  5045.5 2187.86  5050.2 2188.03
  5092.9 2213.58  5107.1 2218.44  5177.3 2232.76  5268.9 2256.57  5273.8 2256.57
#Mann= 4 ,-1 , 0
  4752.3     .07       0  4873.3     .16       0  5041.5     .07       0
  5045.5     .16       0
Bank Sta=5041.5,5045.5
XS Rating Curve= 0 ,0
Exp/Cntr=0.3,0.1

Type RM Length L Ch R = 1 ,17297   ,69,69,69
BEGIN DESCRIPTION:
Elm 74 17296.7
END DESCRIPTION:
XS GIS Cut Line= 3
      1526120.57      6760994.93      1526315.86      6760853.89
      1526471.01      6760664.26
#Sta/Elev= 30
  4755.7 2239.37  4777.9 2238.22  4825.7 2231.63  4863.7 2220.03  4878.4 2212.29
  4893.2 2208.29  4934.9 2204.94  4958.2 2204.74  4964.3 2201.57  4970.9 2195.31
    4979 2189.86  4985.2 2189.06    4991 2185.68  4991.2 2185.18    4995 2185.68
  5000.4 2185.69  5006.9 2188.94  5014.8 2186.79  5021.3 2193.28  5029.1 2189.29
  5035.6 2197.57    5050 2193.16  5056.4 2201.08  5070.8  2205.7  5085.1 2206.52
  5107.4 2212.78  5113.8 2213.01  5171.3 2224.98  5235.2 2244.04  5241.6 2247.11
#Mann= 4 ,-1 , 0
  4755.7     .07       0  4825.7     .16       0    4991     .07       0
    4995     .16       0
Bank Sta=4991,4995
XS Rating Curve= 0 ,0
Exp/Cntr=0.3,0.1

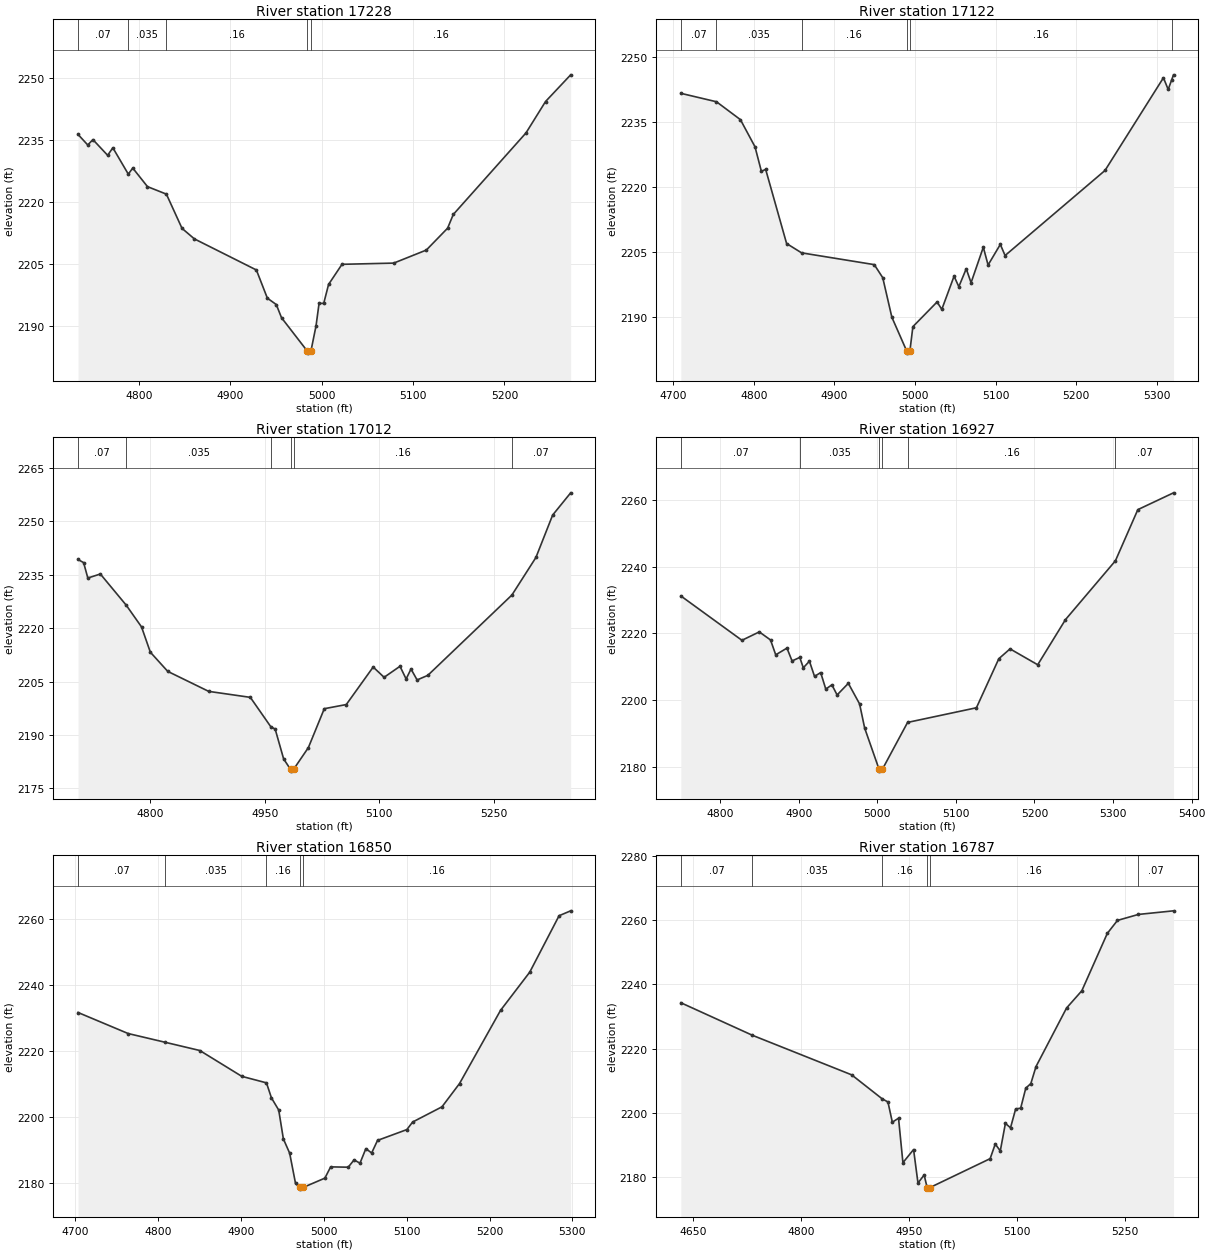
Type RM Length L Ch R = 1 ,17228   ,106,106,106
BEGIN DESCRIPTION:
Elm 74 17227.55
END DESCRIPTION:
XS GIS Cut Line= 3
      1526133.53      6761029.69      1526365.77      6760901.63
       1526524.2      6760678.09
#Sta/Elev= 30
  4733.3 2236.36  4743.9 2233.82  4749.6 2235.11  4765.7 2231.32  4771.4 2233.14
  4788.3 2226.78  4793.2 2228.24  4809.3 2223.76    4830 2221.95  4847.1 2213.69
  4860.6 2211.15  4928.5 2203.64  4940.5 2196.84  4950.3 2195.29    4956 2192.12
  4984.2 2184.07  4984.5 2183.57  4988.2 2184.07  4993.8 2190.17  4997.1 2195.58
  5002.2 2195.58  5007.5 2200.15  5022.2 2205.01  5078.8  2205.3  5114.5 2208.45
  5137.8 2213.73    5144 2217.04  5223.6 2236.73    5245 2244.31  5272.5 2250.75
#Mann= 5 ,-1 , 0
  4733.3     .07       0  4788.3    .035       0    4830     .16       0
  4984.2     .07       0  4988.2     .16       0
Bank Sta=4984.2,4988.2
XS Rating Curve= 0 ,0
Exp/Cntr=0.3,0.1

Type RM Length L Ch R = 1 ,17122   ,110,110,110
BEGIN DESCRIPTION:
Elm 74 17121.75
END DESCRIPTION:
XS GIS Cut Line= 3
      1526137.89       6761086.1      1526411.34      6760992.78
      1526586.65      6760722.25
#Sta/Elev= 30
  4709.4 2241.55  4753.6  2239.6  4783.3 2235.47  4801.4  2229.2  4809.3 2223.53
  4814.6    2224  4840.6 2206.87  4859.2 2204.72  4949.4    2202  4959.9 2198.98
  4971.2 2189.86  4989.6 2182.07  4989.9 2181.57  4993.6 2182.07  4997.3 2187.68
  5027.3 2193.38  5033.2 2191.68  5048.4 2199.33  5054.3  2196.9  5063.5 2201.05
  5069.5 2197.83  5084.7 2206.02  5090.6 2201.91  5105.8 2206.67  5111.7  2204.1
  5235.7 2223.74  5308.2 2245.14  5314.1 2242.44  5318.3 2244.59  5320.7 2245.82
#Mann= 6 ,-1 , 0
  4709.4     .07       0  4753.6    .035       0  4859.2     .16       0
  4989.6     .07       0  4993.6     .16       0  5318.3     .07       0
Bank Sta=4989.6,4993.6
XS Rating Curve= 0 ,0
Exp/Cntr=0.3,0.1

Type RM Length L Ch R = 1 ,17012   ,85,85,85
BEGIN DESCRIPTION:
Elm 74 17012.11
END DESCRIPTION:
XS GIS Cut Line= 3
      1526218.23      6761188.08       1526487.3       6761070.9
      1526760.37      6760849.85
#Sta/Elev= 30
  4705.7 2239.29    4713  2238.4  4718.5 2234.08  4734.9 2235.21  4768.8 2226.44
  4788.8 2220.34  4800.3 2213.25  4823.1 2207.85  4876.7 2202.23  4931.2 2200.55
  4958.1 2192.26  4963.7 2191.64  4974.8 2183.25  4983.8 2180.32    4984 2179.82
  4987.8 2180.32  5007.2 2186.44    5028 2197.36  5056.8 2198.53    5092 2209.07
  5106.3 2206.18  5127.1 2209.28  5135.1 2205.71  5141.5 2208.51  5149.5 2205.44
  5163.5 2206.73  5273.6 2229.31    5305 2239.85  5326.9 2251.77  5350.5 2258.02
#Mann= 6 ,-1 , 0
  4705.7     .07       0  4768.8    .035       0  4958.1     .16       0
  4983.8     .07       0  4987.8     .16       0  5273.6     .07       0
Bank Sta=4983.8,4987.8
XS Rating Curve= 0 ,0
Exp/Cntr=0.3,0.1

Type RM Length L Ch R = 1 ,16927   ,77,77,77
BEGIN DESCRIPTION:
Elm 74 16926.8
END DESCRIPTION:
XS GIS Cut Line= 3
      1526357.08      6761290.09      1526554.57      6761125.16
      1526793.31      6760843.01
#Sta/Elev= 30
    4750 2231.21  4827.7 2217.92  4849.8 2220.44  4864.1 2218.02  4870.7 2213.57
    4885 2215.58  4891.5 2211.73  4901.3 2212.79  4905.8 2209.68  4913.6 2211.66
  4920.1  2207.1  4927.9 2208.25  4934.4  2203.3  4942.2 2204.57  4948.8 2201.54
  4963.1 2205.02  4977.4 2198.87  4983.9  2191.6  5002.3 2179.21  5002.6 2178.71
  5006.3 2179.21  5038.5 2193.31  5126.1  2197.7  5154.6  2212.4  5168.9 2215.35
  5204.1 2210.59  5239.4 2224.11    5303 2241.76  5331.5 2257.08  5376.9 2262.12
#Mann= 6 ,-1 , 0
    4750     .07       0  4901.3    .035       0  5002.3    .035       0
  5006.3    .035       0  5038.5     .16       0    5303     .07       0
Bank Sta=5002.3,5006.3
XS Rating Curve= 0 ,0
Exp/Cntr=0.3,0.1

Type RM Length L Ch R = 1 ,16850   ,63,63,63
BEGIN DESCRIPTION:
Elm 74 16850.34
END DESCRIPTION:
XS GIS Cut Line= 3
      1526385.29      6761313.97      1526589.29       6761172.9
       1526834.5       6760927.7
#Sta/Elev= 30
  4703.2 2231.65  4763.7 2225.29    4808 2222.67  4850.2 2220.16  4900.9 2212.35
  4930.7 2210.38  4936.7 2205.84  4945.5 2202.15  4951.1 2193.44  4958.7 2189.12
  4965.8 2179.96  4970.9 2178.75  4971.1 2178.25  4974.9 2178.75  5001.2 2181.57
  5008.2 2184.98  5029.4 2184.88  5036.5 2187.09  5043.6 2186.09  5050.7 2190.49
  5057.7 2189.18  5064.8 2192.98  5100.2 2196.25  5107.2 2198.54  5142.6 2203.13
  5163.8 2210.17  5213.3 2232.29  5248.6 2243.86    5284 2260.91    5298 2262.39
#Mann= 5 ,-1 , 0
  4703.2     .07       0    4808    .035       0  4930.7     .16       0
  4970.9     .07       0  4974.9     .16       0
Bank Sta=4970.9,4974.9
XS Rating Curve= 0 ,0
Exp/Cntr=0.3,0.1

Type RM Length L Ch R = 1 ,16787   ,92,92,92
BEGIN DESCRIPTION:
Elm 74 16786.88
END DESCRIPTION:
XS GIS Cut Line= 3
      1526389.64      6761353.02      1526691.29      6761136.01
      1526910.04      6760912.98
#Sta/Elev= 30
  4633.4 2234.26  4732.8 2224.13  4870.5 2211.83  4912.9 2204.36  4920.9 2203.39
    4927 2197.09  4935.6 2198.33  4941.7 2184.49  4956.5 2188.58  4962.6 2178.17
  4971.2 2180.66  4975.3 2176.76  4975.6 2176.26  4979.3 2176.76  5062.8 2185.74
  5069.9 2190.29  5076.9 2188.16    5084 2196.72  5091.1 2195.35  5098.2 2201.19
  5105.2 2201.46  5112.3 2207.69  5119.3 2209.11  5126.5 2214.41  5168.9 2232.62
  5190.1 2237.99  5225.5 2255.85  5239.6 2259.89  5268.7 2261.75  5317.4 2262.87
#Mann= 6 ,-1 , 0
  4633.4     .07       0  4732.8    .035       0  4912.9     .16       0
  4975.3     .07       0  4979.3     .16       0  5268.7     .07       0
Bank Sta=4975.3,4979.3
XS Rating Curve= 0 ,0
Exp/Cntr=0.3,0.1