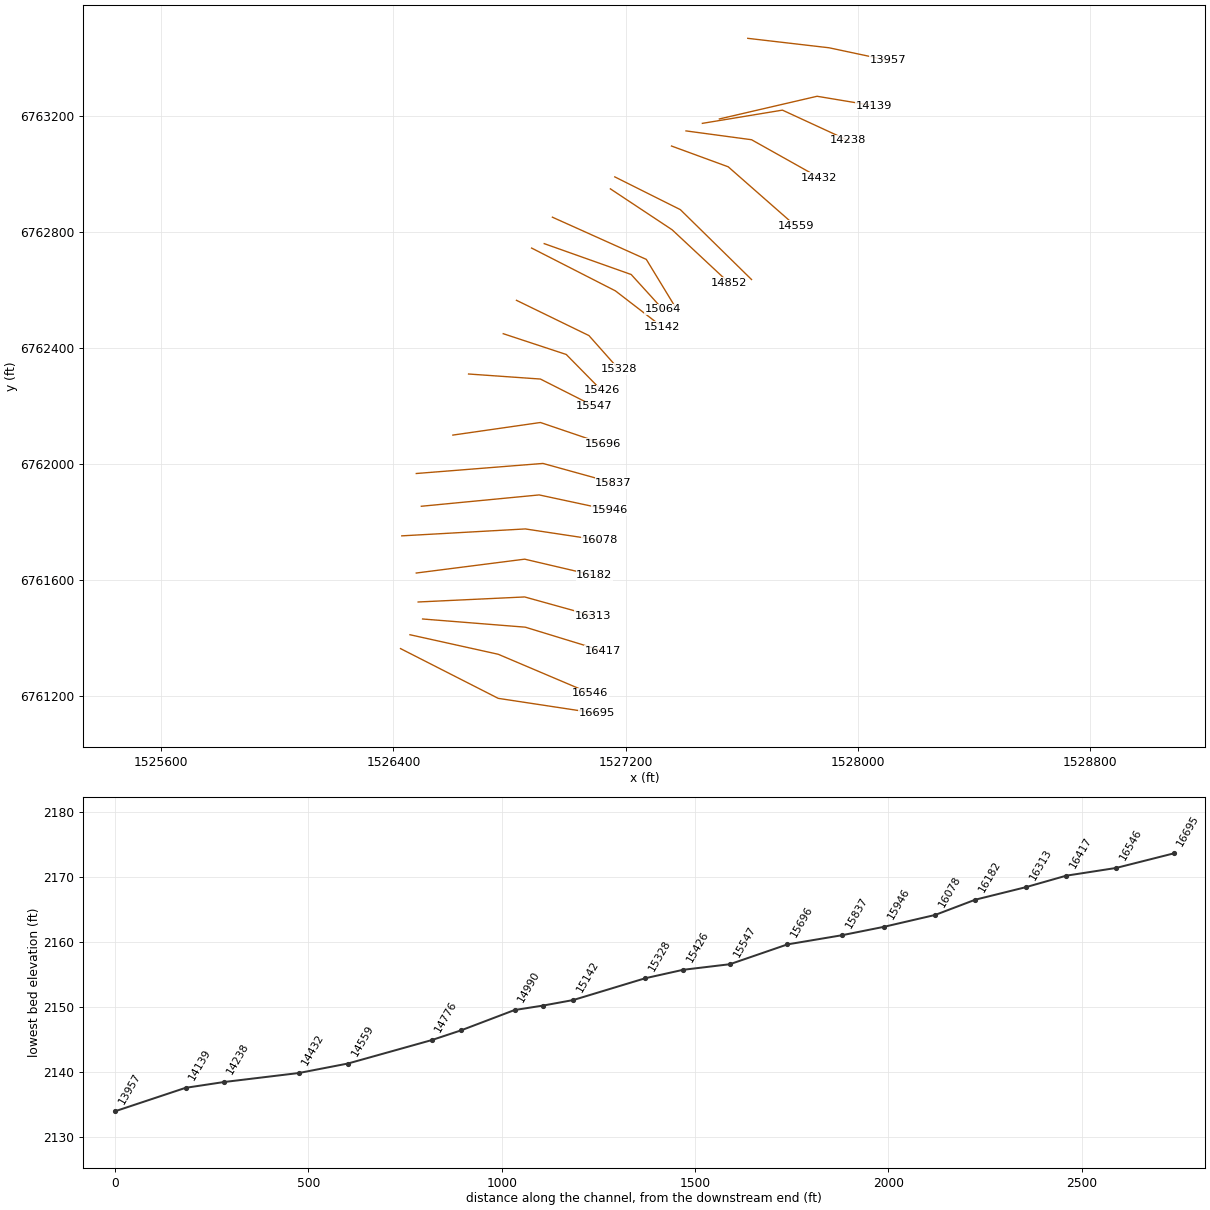
HEC-RAS study Elm 74.prj: Elm 74 Base Level Engineering

--- Elm 74.g01 (geometry) --- (continued)

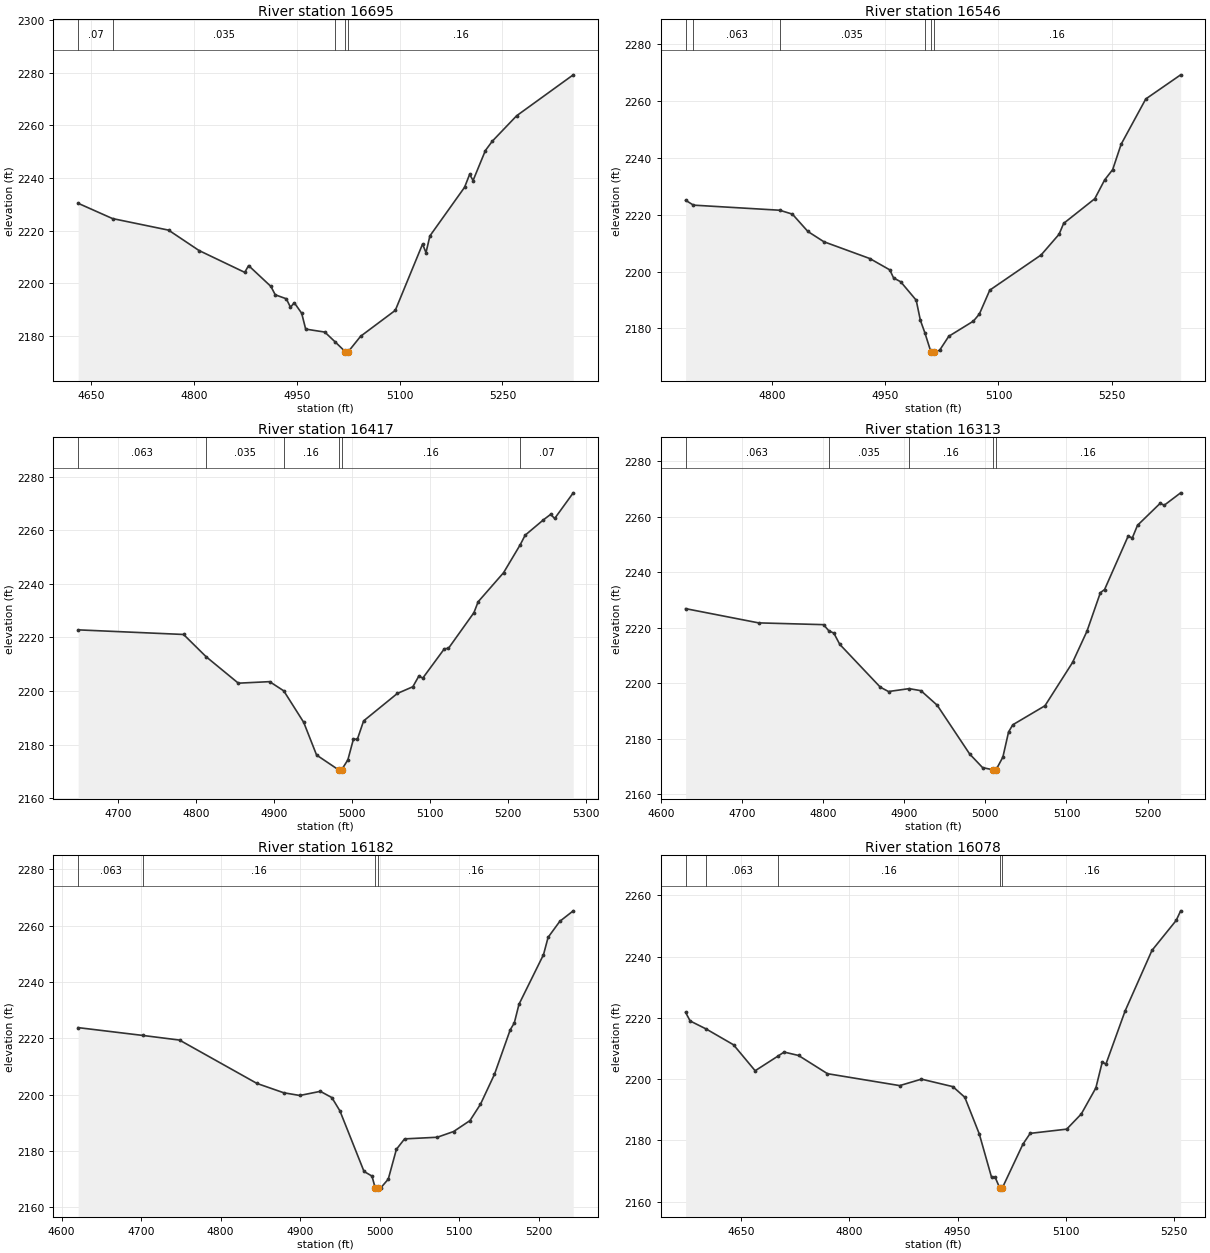
Type RM Length L Ch R = 1 ,16695   ,149,149,149
BEGIN DESCRIPTION:
Elm 74 16694.59
END DESCRIPTION:
XS GIS Cut Line= 3
      1526424.36      6761363.87      1526760.74      6761192.43
      1527101.78      6761140.63
#Sta/Elev= 30
  4630.9 2230.43    4681 2224.64  4762.8 2220.25  4807.3 2212.51    4874 2204.22
  4879.6  2206.8  4912.2 2198.88  4918.5 2195.71  4934.7 2194.19  4940.7 2190.99
  4946.3 2192.68  4957.1  2188.7  4962.9 2182.69  4990.8 2181.56  5005.7 2177.89
  5020.9 2174.07  5021.1 2173.57  5024.9 2174.07  5043.1 2179.97  5093.7  2189.8
  5133.5 2214.95  5138.5 2211.71  5144.2 2218.05  5194.8 2236.51  5202.2 2241.44
  5207.2 2239.08  5225.2 2250.47  5235.3 2254.01  5270.8 2263.66  5353.4 2279.19
#Mann= 5 ,-1 , 0
  4630.9     .07       0    4681    .035       0  5005.7     .16       0
  5020.9    .035       0  5024.9     .16       0
Bank Sta=5020.9,5024.9
XS Rating Curve= 0 ,0
Exp/Cntr=0.3,0.1

Type RM Length L Ch R = 1 ,16546   ,129,129,129
BEGIN DESCRIPTION:
Elm 74 16545.58
END DESCRIPTION:
XS GIS Cut Line= 3
       1526456.9      6761411.62      1526760.74      6761344.34
      1527077.56       6761209.8
#Sta/Elev= 30
  4685.8 2225.03  4696.2 2223.31  4810.4 2221.52  4827.2 2220.15  4847.7 2214.06
  4868.9 2210.45  4929.7 2204.55  4956.1 2200.58  4961.2 2197.73  4970.6 2196.39
  4991.1 2189.92  4996.6  2182.9  5002.6 2178.45  5010.5 2171.83  5010.7 2171.33
  5014.5 2171.83    5022  2172.3  5034.2 2177.24  5066.8 2182.57  5074.7 2185.05
  5088.5 2193.45  5156.5 2205.82  5180.2 2213.07  5186.3  2216.9  5227.5 2225.56
  5240.6 2232.18  5251.2 2235.79  5262.4  2244.7    5295  2260.6  5341.2 2269.08
#Mann= 6 ,-1 , 0
  4685.8     .07       0  4696.2    .063       0  4810.4    .035       0
  5002.6     .16       0  5010.5    .035       0  5014.5     .16       0
Bank Sta=5010.5,5014.5
XS Rating Curve= 0 ,0
Exp/Cntr=0.3,0.1

Type RM Length L Ch R = 1 ,16417   ,104,104,104
BEGIN DESCRIPTION:
Elm 74 16416.53
END DESCRIPTION:
XS GIS Cut Line= 3
      1526500.36      6761465.87      1526854.05      6761437.66
      1527121.56      6761355.68
#Sta/Elev= 30
  4648.9 2222.84    4784 2221.12  4812.9 2212.82  4854.2 2202.95  4894.3 2203.52
  4912.4  2200.1    4938 2188.34  4954.5 2176.14  4982.6 2170.64  4982.9 2170.14
  4986.6 2170.64  4994.6 2174.34  5001.7 2182.05  5006.8 2182.05  5014.8 2188.88
    5058 2199.11  5077.9 2201.62  5085.5 2205.56  5090.7 2204.87  5118.3 2215.79
  5123.5 2215.93  5156.2 2229.26  5161.6 2233.32  5194.2 2244.17  5215.6 2254.62
  5221.8 2258.14  5245.3 2263.89  5254.5 2265.92  5259.7 2264.39  5283.5 2273.96
#Mann= 6 ,-1 , 0
  4648.9    .063       0  4812.9    .035       0  4912.4     .16       0
  4982.6     .07       0  4986.6     .16       0  5215.6     .07       0
Bank Sta=4982.6,4986.6
XS Rating Curve= 0 ,0
Exp/Cntr=0.3,0.1

Type RM Length L Ch R = 1 ,16313   ,131,131,131
BEGIN DESCRIPTION:
Elm 74 16312.71
END DESCRIPTION:
XS GIS Cut Line= 3
      1526485.13      6761524.46      1526851.88      6761541.82
      1527086.24      6761476.72
#Sta/Elev= 30
  4630.4 2226.94  4720.4 2221.81  4800.5 2221.17    4807 2218.95  4813.2 2218.12
  4820.5 2214.07  4870.5 2198.63  4880.6 2197.07    4906 2198.11  4920.6 2197.37
  4940.6 2192.14  4980.7 2174.54  4996.6 2169.64  5009.2 2168.88  5009.4 2168.38
  5013.2 2168.88  5021.6 2173.43  5028.6 2182.48  5033.8 2185.08  5073.5 2191.94
  5107.5 2207.54  5125.3 2218.82  5141.8 2232.69    5147 2233.83    5176 2253.04
  5181.2 2252.44  5187.6 2256.98  5215.5 2264.89  5220.6 2264.22  5240.8 2268.68
#Mann= 5 ,-1 , 0
  4630.4    .063       0    4807    .035       0    4906     .16       0
  5009.2     .07       0  5013.2     .16       0
Bank Sta=5009.2,5013.2
XS Rating Curve= 0 ,0
Exp/Cntr=0.3,0.1

Type RM Length L Ch R = 1 ,16182   ,104,104,104
BEGIN DESCRIPTION:
Elm 74 16182.49
END DESCRIPTION:
XS GIS Cut Line= 3
      1526478.64      6761624.29      1526851.88      6761672.03
      1527091.42      6761615.93
#Sta/Elev= 30
  4620.9 2223.79  4702.6    2221  4748.3 2219.37  4845.6 2203.98  4879.3 2200.66
  4899.5  2199.7  4925.3 2201.17  4939.8 2198.95  4949.9 2194.24  4980.2 2172.73
  4990.2 2171.08  4994.2 2166.95  4994.5 2166.45  4998.2 2166.95  5001.4 2166.95
  5010.7    2170  5020.9 2180.58  5031.2 2184.29  5072.3 2184.87  5092.8  2186.9
  5113.4 2190.79  5126.6  2196.6  5144.2 2207.23    5164 2223.04  5169.1 2225.44
    5175 2232.09  5205.8 2249.69  5211.6 2255.85  5226.3 2261.53  5243.2 2265.26
#Mann= 4 ,-1 , 0
  4620.9    .063       0  4702.6     .16       0  4994.2     .07       0
  4998.2     .16       0
Bank Sta=4994.2,4998.2
XS Rating Curve= 0 ,0
Exp/Cntr=0.3,0.1

Type RM Length L Ch R = 1 ,16078   ,132,132,132
BEGIN DESCRIPTION:
Elm 74 16077.82
END DESCRIPTION:
XS GIS Cut Line= 3
      1526428.72      6761752.33      1526854.05       6761776.2
      1527111.13      6761737.31
#Sta/Elev= 30
  4573.1 2221.82  4579.4 2218.99  4601.8 2216.35  4639.5 2211.22  4669.5 2202.74
  4700.8 2207.48  4709.6 2208.84  4729.6 2207.73  4769.7 2201.78  4869.8 2197.89
  4899.9    2200  4943.5 2197.55    4960 2194.08    4980 2182.16  4997.1 2167.93
  5002.1 2167.93  5008.2  2164.6  5008.4  2164.1  5012.2  2164.6  5040.5 2178.76
  5050.6  2182.3  5101.2 2183.68  5121.4 2188.63  5141.6 2197.13  5150.5 2205.62
  5155.5 2204.88  5182.1 2222.24  5219.3 2242.01  5252.9 2251.81  5259.1 2254.94
#Mann= 5 ,-1 , 0
  4573.1     .07       0  4601.8    .063       0  4700.8     .16       0
  5008.2     .07       0  5012.2     .16       0
Bank Sta=5008.2,5012.2
XS Rating Curve= 0 ,0
Exp/Cntr=0.3,0.1

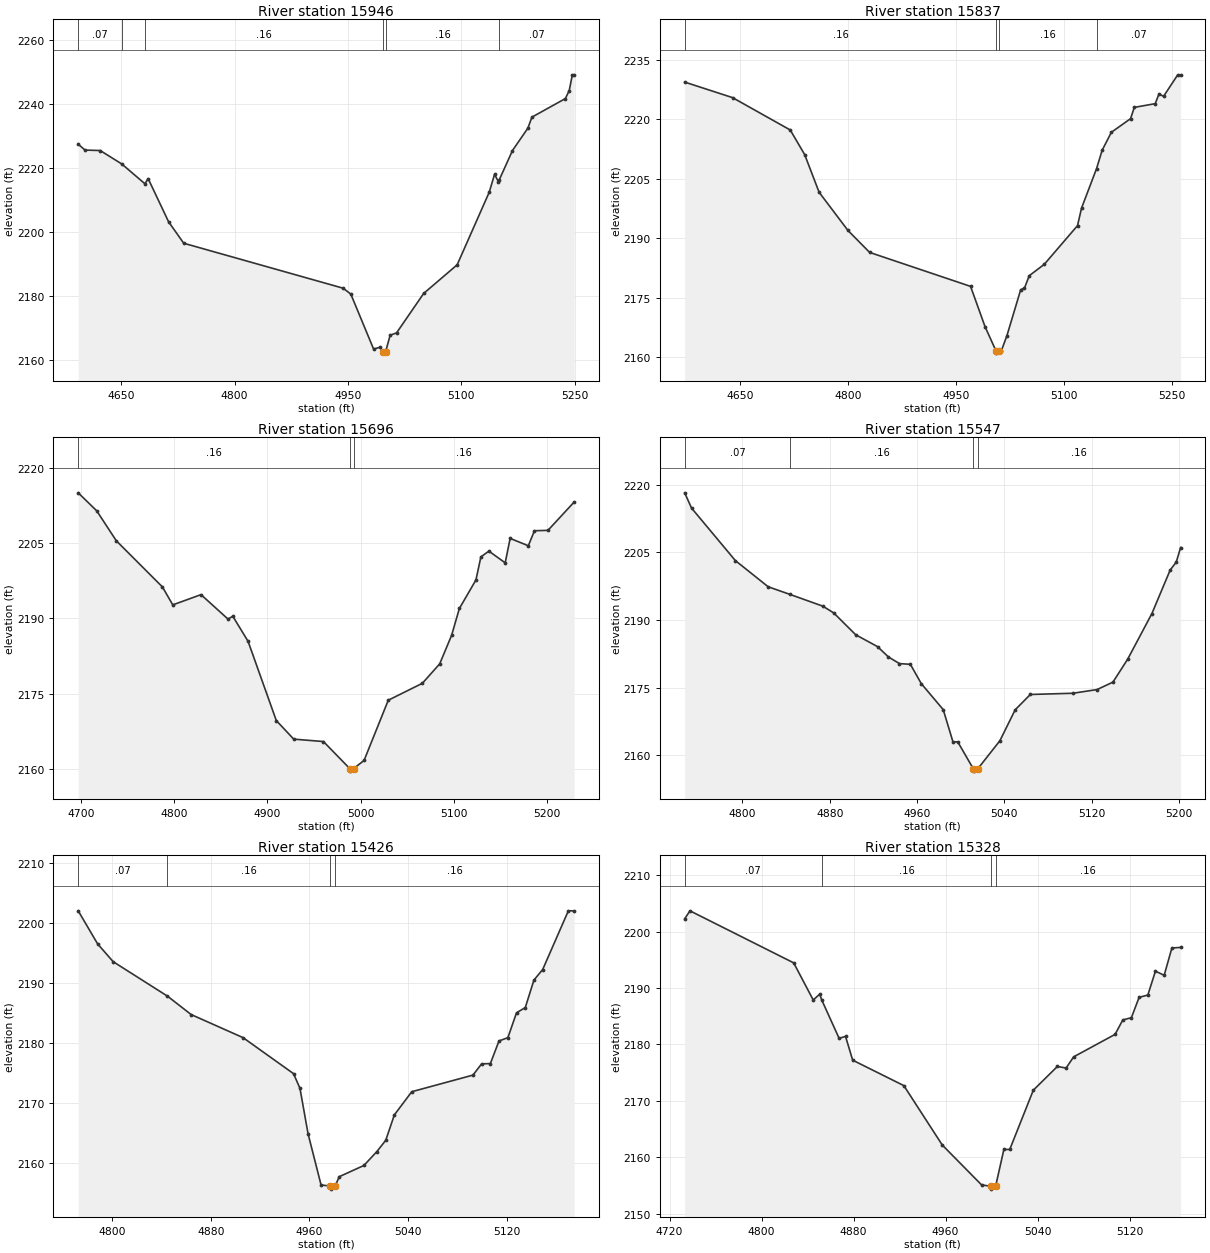
Type RM Length L Ch R = 1 ,15946   ,109,109,109
BEGIN DESCRIPTION:
Elm 74 15945.68
END DESCRIPTION:
XS GIS Cut Line= 3
        1526496.      6761854.33      1526901.79      6761893.39
      1527144.81      6761841.31
#Sta/Elev= 30
  4593.2 2227.51  4602.2 2225.66  4622.3 2225.52  4650.8 2221.33  4681.5 2215.14
  4685.7 2216.77  4712.8 2203.27  4732.8 2196.58  4943.8 2182.54  4953.9  2180.7
    4984 2163.57  4992.9 2164.12    4996 2162.78  4996.2 2162.28    5000 2162.78
    5006 2167.89  5014.4 2168.59  5050.3 2180.91  5094.6 2189.85  5137.1 2212.55
  5144.1 2218.09  5149.2 2215.78  5150.5 2216.47  5167.8 2225.52  5188.2 2232.51
  5193.5 2235.94  5237.8 2241.74  5242.9 2244.25    5247 2249.15  5249.4 2249.15
#Mann= 6 ,-1 , 0
  4593.2     .07       0  4650.8    .063       0  4681.5     .16       0
    4996     .07       0    5000     .16       0  5150.5     .07       0
Bank Sta=4996,5000
XS Rating Curve= 0 ,0
Exp/Cntr=0.3,0.1

Type RM Length L Ch R = 1 ,15837   ,141,141,141
BEGIN DESCRIPTION:
Elm 74 15837.29
END DESCRIPTION:
XS GIS Cut Line= 3
      1526478.65      6761967.17      1526914.82      6762001.89
      1527157.83      6761934.63
#Sta/Elev= 30
  4572.8 2229.33  4639.4 2225.41  4719.6 2217.25  4739.7 2211.04  4759.7 2201.56
  4799.9 2191.91    4830 2186.38  4970.4 2177.81  4990.5 2167.66  5005.9 2161.48
  5006.2 2160.98  5009.9 2161.48    5013 2161.48  5020.9 2165.36  5040.1 2176.97
  5045.3 2177.35    5052 2180.51  5072.8 2183.36  5119.1 2193.13  5124.7 2197.54
  5145.6 2207.51  5153.4 2212.15  5166.2 2216.67  5192.9 2220.11  5198.1 2222.95
  5227.2 2223.89  5232.4 2226.33  5238.8 2225.74  5258.5 2231.16  5262.5 2231.16
#Mann= 4 ,-1 , 0
  4572.8     .16       0  5005.9     .07       0  5009.9     .16       0
  5145.6     .07       0
Bank Sta=5005.9,5009.9
XS Rating Curve= 0 ,0
Exp/Cntr=0.3,0.1

Type RM Length L Ch R = 1 ,15696   ,149,149,149
BEGIN DESCRIPTION:
Elm 74 15695.64
END DESCRIPTION:
XS GIS Cut Line= 3
      1526604.53      6762099.56      1526906.13      6762142.95
      1527121.61      6762069.69
#Sta/Elev= 30
  4696.9 2214.98  4716.8 2211.39  4737.8 2205.43  4787.3 2196.24  4798.4 2192.67
  4828.7 2194.71  4857.7 2189.84  4862.8 2190.41  4879.2 2185.42  4909.5 2169.64
  4928.2 2165.94  4960.1 2165.46  4988.4 2160.07  4988.6 2159.57  4992.4 2160.07
  5003.7 2161.69  5029.7 2173.69  5066.3 2177.06  5084.9 2180.93  5097.7 2186.62
    5106 2191.95  5123.8 2197.64  5129.1 2202.23  5137.7 2203.37  5155.2 2201.04
  5160.5 2205.91    5180 2204.44  5186.6 2207.43  5201.1 2207.51  5229.2 2213.15
#Mann= 3 ,-1 , 0
  4696.9     .16       0  4988.4     .07       0  4992.4     .16       0
Bank Sta=4988.4,4992.4
XS Rating Curve= 0 ,0
Exp/Cntr=0.3,0.1

Type RM Length L Ch R = 1 ,15547   ,121,121,121
BEGIN DESCRIPTION:
Elm 74 15547.08
END DESCRIPTION:
XS GIS Cut Line= 3
      1526658.72      6762310.06      1526906.13      6762292.69
      1527090.29      6762199.53
#Sta/Elev= 30
  4747.1 2218.17  4753.4 2214.79  4793.5 2203.17  4823.6 2197.36  4843.8 2195.65
  4873.7 2193.06  4883.7 2191.56  4903.8 2186.73  4923.8  2184.1  4933.8 2181.81
  4943.9 2180.34  4953.9 2180.18  4963.9  2175.9    4984 2170.14  4992.9 2163.01
  4997.3 2163.01  5011.6 2157.02  5011.9 2156.52  5015.6 2157.02  5035.9 2163.25
  5049.9  2170.1  5063.8  2173.5  5102.8 2173.77    5125 2174.59  5139.5 2176.24
  5152.9 2181.28  5175.2 2191.43  5191.9 2201.05  5197.5 2202.83  5201.5 2206.05
#Mann= 4 ,-1 , 0
  4747.1     .07       0  4843.8     .16       0  5011.6     .07       0
  5015.6     .16       0
Bank Sta=5011.6,5015.6
XS Rating Curve= 0 ,0
Exp/Cntr=0.3,0.1

Type RM Length L Ch R = 1 ,15426   ,98,98,98
BEGIN DESCRIPTION:
Elm 74 15426.2
END DESCRIPTION:
XS GIS Cut Line= 3
      1526778.13      6762448.93      1526995.11      6762377.33
      1527116.64      6762253.63
#Sta/Elev= 30
  4772.6 2202.03  4788.3 2196.53  4800.9 2193.56  4844.9 2187.82  4864.1 2184.75
  4906.2  2180.9  4947.1  2174.9  4952.3 2172.45  4958.9 2164.85  4969.4 2156.36
  4976.8 2156.16  4977.1 2155.66  4980.8 2156.16  4984.1 2157.73  5004.1  2159.6
  5014.6 2161.91  5021.8 2163.79  5028.8 2168.03  5042.9 2171.89  5092.5 2174.66
  5099.5 2176.53  5106.6 2176.58  5113.6 2180.35  5120.8  2180.9  5127.8 2185.04
  5134.9 2185.91  5141.9 2190.49    5149 2192.25  5169.8 2202.03  5174.5 2202.03
#Mann= 4 ,-1 , 0
  4772.6     .07       0  4844.9     .16       0  4976.8     .07       0
  4980.8     .16       0
Bank Sta=4976.8,4980.8
XS Rating Curve= 0 ,0
Exp/Cntr=0.3,0.1

Type RM Length L Ch R = 1 ,15328   ,186,186,186
BEGIN DESCRIPTION:
Elm 74 15327.93
END DESCRIPTION:
XS GIS Cut Line= 3
      1526823.65      6762563.97      1527073.24      6762442.43
      1527175.21      6762327.44
#Sta/Elev= 30
  4733.1 2202.25  4737.7 2203.67  4827.9 2194.45  4844.9 2187.87  4850.5  2188.9
  4852.4 2187.83  4867.4 2181.08    4873 2181.42  4879.2 2177.21  4923.7  2172.7
  4957.1 2162.18  4991.3 2155.11  4999.5 2154.86  4999.8 2154.36  5003.5 2154.86
  5010.7 2161.39  5015.8 2161.39  5036.3 2171.89  5057.2 2176.09  5064.8 2175.82
  5071.4  2177.8  5107.4 2181.78  5114.1 2184.33  5121.6 2184.74  5128.3 2188.34
  5135.9 2188.75  5142.5 2192.98  5150.1 2192.25  5156.8 2197.08  5164.4 2197.19
#Mann= 4 ,-1 , 0
  4733.1     .07       0  4852.4     .16       0  4999.5     .07       0
  5003.5     .16       0
Bank Sta=4999.5,5003.5
XS Rating Curve= 0 ,0
Exp/Cntr=0.3,0.1

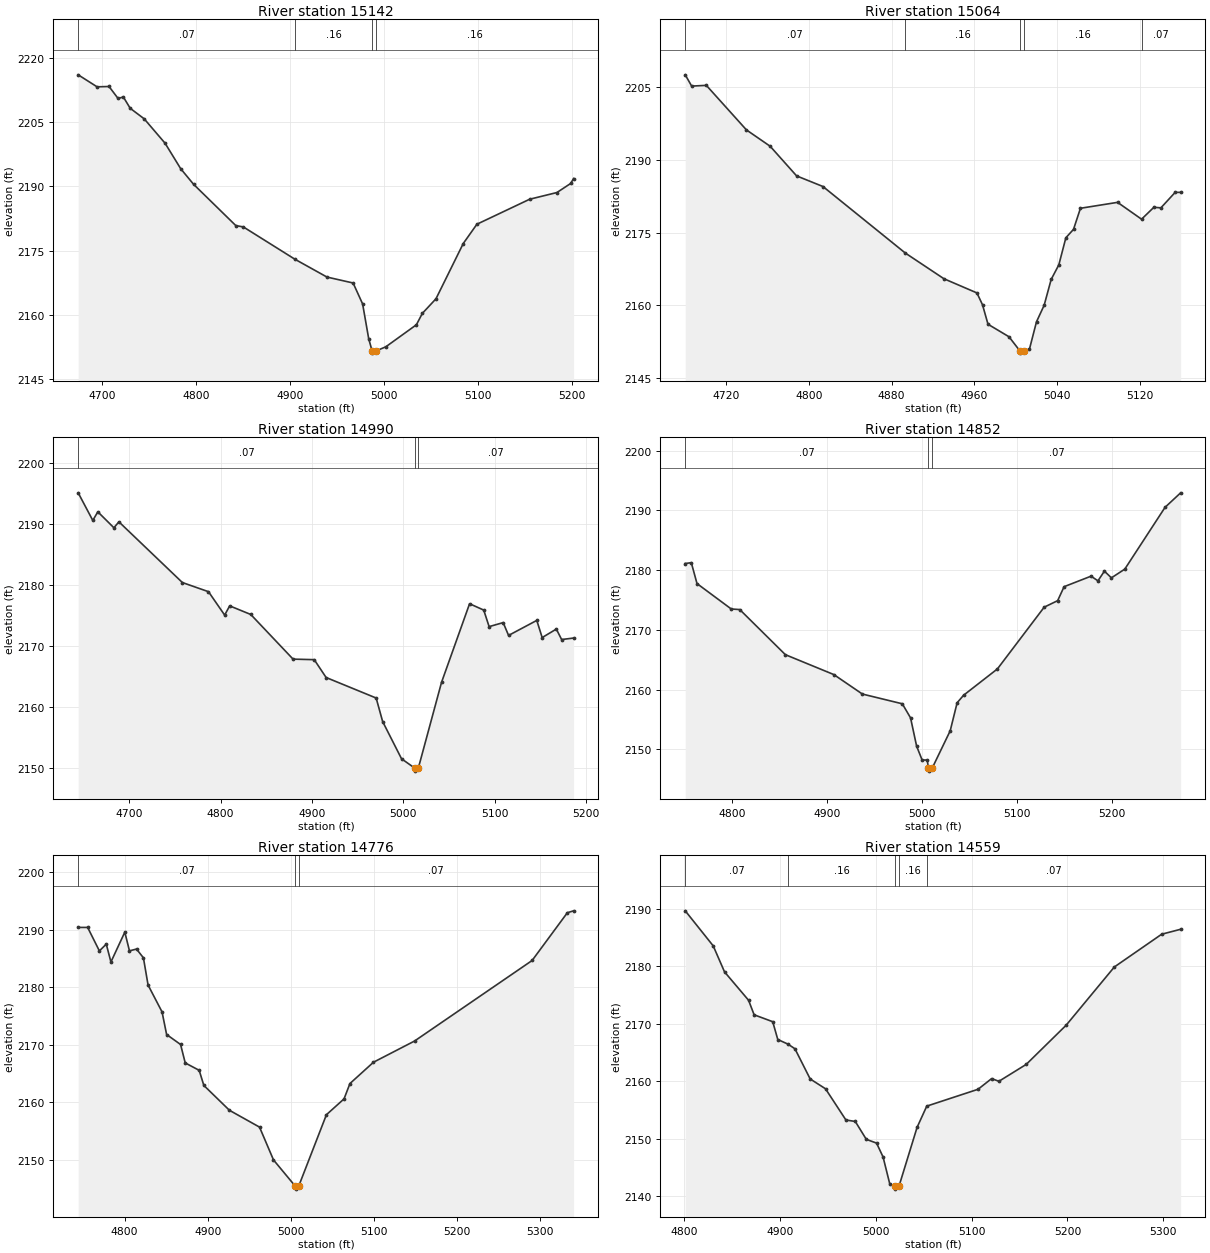
Type RM Length L Ch R = 1 ,15142   ,78,78,78
BEGIN DESCRIPTION:
Elm 74 15141.57
END DESCRIPTION:
XS GIS Cut Line= 3
      1526875.78      6762744.07      1527164.38      6762596.51
      1527324.86       6762472.9
#Sta/Elev= 30
    4675 2216.13  4695.1 2213.32  4707.8  2213.4  4717.4  2210.6    4723 2210.95
  4730.3  2208.3  4745.2 2205.83  4767.4 2200.12    4784 2194.16  4797.7 2190.51
  4842.6 2180.85  4850.6 2180.54  4905.5 2172.97  4939.5 2168.81  4967.3 2167.42
  4977.4 2162.52  4983.9 2154.35  4987.5 2151.51  4987.8 2151.01  4991.5 2151.51
    5002 2152.48  5034.6 2157.65  5040.9 2160.31  5055.4 2163.73  5084.4 2176.66
  5098.9 2181.17    5155 2187.02    5184 2188.59  5198.6 2190.71  5201.7 2191.87
#Mann= 4 ,-1 , 0
    4675     .07       0  4905.5     .16       0  4987.5     .07       0
  4991.5     .16       0
Bank Sta=4987.5,4991.5
XS Rating Curve= 0 ,0
Exp/Cntr=0.3,0.1

Type RM Length L Ch R = 1 ,15064   ,74,74,74
BEGIN DESCRIPTION:
Elm 74 15063.5
END DESCRIPTION:
XS GIS Cut Line= 3
       1526919.2      6762759.26      1527218.63      6762652.94
      1527327.17      6762533.55
#Sta/Elev= 30
  4680.4 2207.49  4686.6 2205.17  4700.8 2205.32  4739.6 2196.14  4762.5 2192.78
  4788.1 2186.67  4813.6 2184.48  4893.2 2170.78  4930.6 2165.48  4962.5 2162.56
  4967.9 2160.11  4973.2 2156.11  4993.5 2153.53  5003.9 2150.66  5004.1 2150.16
  5007.9 2150.66  5013.3    2151  5020.1 2156.62  5027.5 2160.02  5034.3 2165.35
  5041.7 2168.35  5048.5 2173.93  5055.9 2175.66  5062.6    2180  5098.5 2181.22
  5121.7 2177.75  5133.6  2180.2  5140.4 2180.09  5154.2 2183.28  5159.5 2183.28
#Mann= 5 ,-1 , 0
  4680.4     .07       0  4893.2     .16       0  5003.9     .07       0
  5007.9     .16       0  5121.7     .07       0
Bank Sta=5003.9,5007.9
XS Rating Curve= 0 ,0
Exp/Cntr=0.3,0.1

Type RM Length L Ch R = 1 ,14990   ,138,138,138
BEGIN DESCRIPTION:
Elm 74 14990.08
END DESCRIPTION:
XS GIS Cut Line= 3
      1526947.37      6762850.42      1527270.72      6762705.02
      1527368.38      6762544.42
#Sta/Elev= 30
  4644.1 2195.04  4660.1 2190.52  4665.6 2191.93  4683.2 2189.32  4688.7 2190.29
  4758.2 2180.35  4786.8 2178.85  4804.5 2175.02    4810 2176.53  4833.1 2175.12
  4879.4 2167.81  4902.6 2167.72  4915.6  2164.8  4970.4 2161.44  4977.5 2157.59
  4998.2 2151.49  5012.6 2149.97  5012.9 2149.47  5016.6 2149.97    5042 2164.01
  5072.7 2176.88  5088.2 2175.84  5094.1 2173.13  5109.5 2173.79  5115.4 2171.69
  5146.3 2174.15  5152.2 2171.34  5167.7 2172.73  5173.5 2171.02  5186.6 2171.26
#Mann= 3 ,-1 , 0
  4644.1     .07       0  5012.6     .07       0  5016.6     .07       0
Bank Sta=5012.6,5016.6
XS Rating Curve= 0 ,0
Exp/Cntr=0.3,0.1

Type RM Length L Ch R = 1 ,14852   ,76,76,76
BEGIN DESCRIPTION:
Elm 74 14851.93
END DESCRIPTION:
XS GIS Cut Line= 3
      1527147.02      6762948.07      1527359.69      6762807.02
      1527555.03       6762624.7
#Sta/Elev= 30
  4750.5  2181.1  4756.9 2181.24  4762.9 2177.74    4799 2173.49    4808 2173.39
  4856.1 2165.84  4907.2 2162.51  4937.3 2159.25  4979.4 2157.62  4988.1 2155.26
  4994.5 2150.52  5000.3 2148.21  5005.7 2148.21  5006.9 2146.85  5007.1 2146.35
  5010.9 2146.85  5029.9  2153.1  5037.2 2157.79    5044 2159.05  5079.7 2163.46
    5129 2173.79  5143.2 2174.88    5150 2177.22  5178.4 2178.98  5185.7  2178.2
  5192.5 2179.82  5199.9  2178.7    5214 2180.16  5256.5 2190.51  5272.9 2192.93
#Mann= 3 ,-1 , 0
  4750.5     .07       0  5006.9     .07       0  5010.9     .07       0
Bank Sta=5006.9,5010.9
XS Rating Curve= 0 ,0
Exp/Cntr=0.3,0.1

Type RM Length L Ch R = 1 ,14776   ,217,217,217
BEGIN DESCRIPTION:
Elm 74 14776.35
END DESCRIPTION:
XS GIS Cut Line= 3
      1527162.21      6762989.31      1527387.91      6762876.46
      1527633.14      6762635.57
#Sta/Elev= 30
  4744.1 2190.43  4755.5 2190.43  4769.6 2186.34  4777.9 2187.52  4783.5 2184.41
  4800.2 2189.61  4805.8 2186.35  4814.3 2186.66  4822.6 2185.13  4828.2 2180.39
    4845 2175.72  4850.5 2171.78  4867.3 2170.04  4872.9 2166.83  4889.7 2165.54
  4895.3 2162.91  4926.1 2158.58  4962.3 2155.65  4979.1 2149.94  5005.4 2145.35
  5005.6 2144.85  5009.4 2145.35  5042.8 2157.81    5064 2160.57  5071.1 2163.24
  5099.4 2166.95  5148.8 2170.64  5290.3 2184.67  5332.7 2192.99  5340.2 2193.32
#Mann= 3 ,-1 , 0
  4744.1     .07       0  5005.4     .07       0  5009.4     .07       0
Bank Sta=5005.4,5009.4
XS Rating Curve= 0 ,0
Exp/Cntr=0.3,0.1

Type RM Length L Ch R = 1 ,14559   ,127,127,127
BEGIN DESCRIPTION:
Elm 74 14559.24
END DESCRIPTION:
XS GIS Cut Line= 3
      1527357.54      6763095.64      1527552.84      6763024.03
      1527785.04      6762820.03
#Sta/Elev= 30
  4801.1 2189.66  4830.3 2183.56  4842.1 2179.04  4867.2  2174.1    4873 2171.57
  4892.4 2170.37  4897.7 2167.27  4908.3 2166.47  4915.6 2165.66  4931.5 2160.41
  4947.5  2158.7  4968.8 2153.27  4978.6 2153.01  4990.1  2149.9  5000.8 2149.25
  5007.6 2146.83  5014.7 2142.07  5020.2 2141.74  5020.5 2141.24  5024.2 2141.74
  5043.1 2151.99  5053.2 2155.68  5106.7 2158.61  5120.9 2160.47  5128.5    2160
    5157 2162.94  5198.7 2169.76    5249 2179.89  5298.4 2185.59  5318.2 2186.45
#Mann= 5 ,-1 , 0
  4801.1     .07       0  4908.3     .16       0  5020.2     .07       0
  5024.2     .16       0  5053.2     .07       0
Bank Sta=5020.2,5024.2
XS Rating Curve= 0 ,0
Exp/Cntr=0.3,0.1

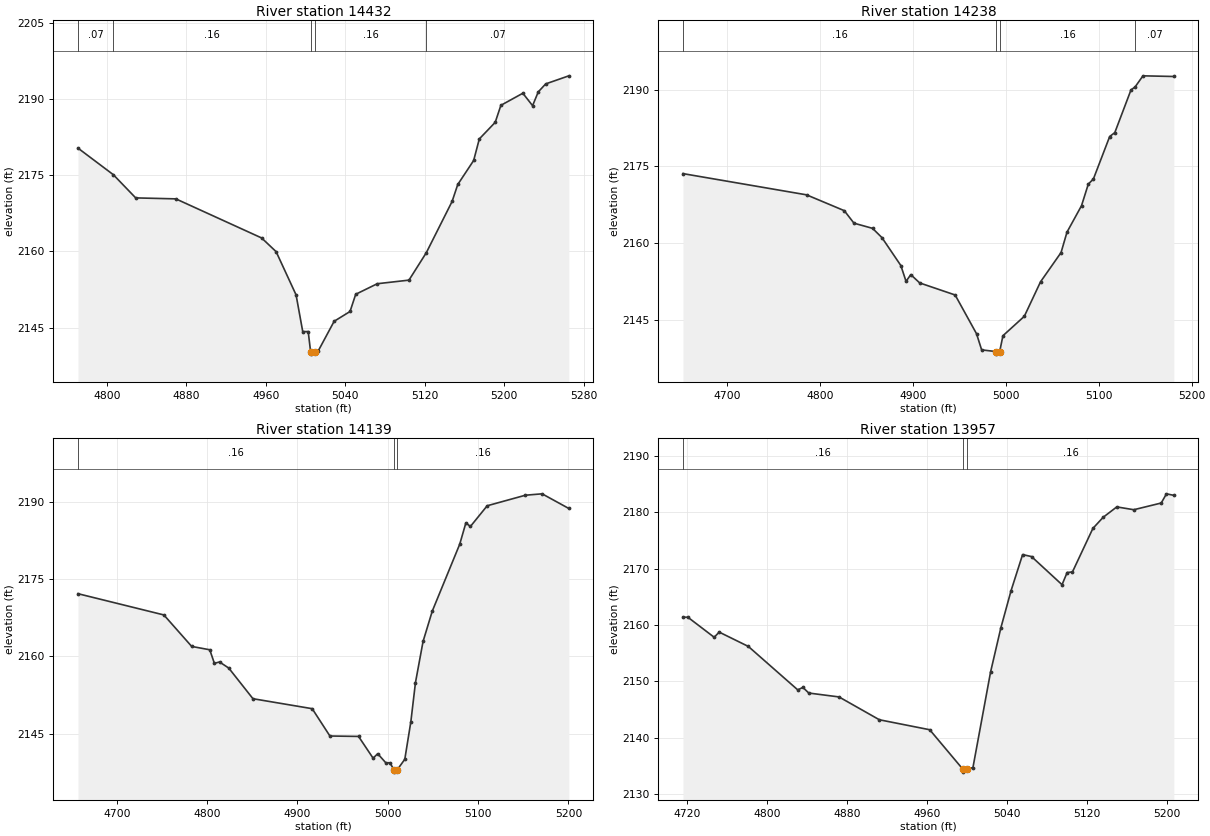
Type RM Length L Ch R = 1 ,14432   ,194,194,194
BEGIN DESCRIPTION:
Elm 74 14432.31
END DESCRIPTION:
XS GIS Cut Line= 3
      1527407.41      6763147.73      1527633.13      6763117.35
      1527865.36      6762987.12
#Sta/Elev= 30
    4771 2180.37  4806.6 2175.13  4829.1 2170.56  4869.5 2170.37  4955.8 2162.67
  4970.4 2159.97  4990.5 2151.45  4997.2 2144.22  5002.7 2144.22  5005.1 2140.28
  5005.4 2139.78  5009.1 2140.28  5012.9 2140.45  5028.8 2146.25  5044.8 2148.18
  5050.5 2151.57  5072.2 2153.65  5104.1 2154.36  5121.6 2159.78  5147.5 2169.86
  5153.2  2173.2  5169.2 2177.93  5174.9 2182.18  5190.9 2185.45  5196.6  2188.8
  5218.7 2191.18  5228.5 2188.73  5234.2 2191.44  5241.7 2193.02    5265 2194.61
#Mann= 5 ,-1 , 0
    4771     .07       0  4806.6     .16       0  5005.1     .07       0
  5009.1     .16       0  5121.6     .07       0
Bank Sta=5005.1,5009.1
XS Rating Curve= 0 ,0
Exp/Cntr=0.3,0.1

Type RM Length L Ch R = 1 ,14238   ,99,99,99
BEGIN DESCRIPTION:
Elm 74 14237.93
END DESCRIPTION:
XS GIS Cut Line= 3
      1527463.84      6763173.77      1527739.47      6763219.34
      1527965.13      6763115.19
#Sta/Elev= 30
  4652.9 2173.61  4785.8 2169.47  4826.4 2166.38  4836.8 2163.94  4856.8 2162.93
  4866.9 2161.12  4887.2 2155.68  4892.8 2152.59  4897.9  2153.9  4907.5 2152.28
  4945.6 2149.93  4968.6 2142.37  4974.1 2139.22  4989.5 2138.89  4989.8 2138.39
  4993.5 2138.89    4997 2141.98    5020 2145.77  5037.4 2152.49  5059.5 2158.21
  5065.9  2162.2  5081.5 2167.35  5088.8 2171.56  5094.3 2172.57  5111.8 2180.85
  5117.3 2181.61  5134.7 2189.94  5139.1 2190.52  5147.6 2192.69  5180.8 2192.56
#Mann= 4 ,-1 , 0
  4652.9     .16       0  4989.5     .07       0  4993.5     .16       0
  5139.1     .07       0
Bank Sta=4989.5,4993.5
XS Rating Curve= 0 ,0
Exp/Cntr=0.3,0.1

Type RM Length L Ch R = 1 ,14139   ,182,182,182
BEGIN DESCRIPTION:
Elm 74 14139.42
END DESCRIPTION:
XS GIS Cut Line= 3
      1527522.41      6763188.95      1527858.83      6763267.09
      1528054.16      6763234.53
#Sta/Elev= 30
  4657.1 2172.18  4752.2 2168.05    4783 2161.93    4803 2161.28  4808.1 2158.65
  4813.8 2158.91    4824 2157.73  4850.8 2151.77  4916.4 2149.83    4936 2144.52
  4967.7 2144.44  4983.8 2140.21  4988.9 2141.08  4997.9 2139.31  5002.5 2139.31
  5006.7    2138    5007  2137.5  5010.7    2138  5018.9    2140  5025.6  2147.3
  5030.7  2154.9  5039.1 2162.89  5049.3 2168.79  5079.7  2181.8  5086.5 2185.94
  5091.5 2185.24  5110.1 2189.27  5152.4 2191.32  5170.9 2191.59  5200.5 2188.74
#Mann= 3 ,-1 , 0
  4657.1     .16       0  5006.7     .07       0  5010.7     .16       0
Bank Sta=5006.7,5010.7
XS Rating Curve= 0 ,0
Exp/Cntr=0.3,0.1

Type RM Length L Ch R = 1 ,13957   ,165,165,165
BEGIN DESCRIPTION:
Elm 74 13956.59
END DESCRIPTION:
XS GIS Cut Line= 3
      1527620.15      6763466.73      1527900.06      6763434.19
       1528104.1      6763390.77
#Sta/Elev= 30
  4716.3 2161.38  4721.2 2161.38  4747.5 2157.82  4752.5 2158.74  4781.6  2156.2
    4831 2148.49  4836.1 2148.93    4842 2147.93  4872.2 2147.24  4912.5 2143.19
  4962.8 2141.42    4996  2134.4  4996.3  2133.9  5000.1  2134.4    5006 2134.72
  5023.6 2151.66  5033.8 2159.44    5044 2166.05  5055.6 2172.49  5064.5 2172.14
    5095 2167.15  5100.1 2169.31  5105.4 2169.41  5125.8 2177.13  5136.1 2179.11
  5149.7 2180.95  5166.7 2180.45  5194.1 2181.64  5199.3 2183.27  5206.7    2183
#Mann= 3 ,-1 , 0
  4716.3     .16       0    4996     .07       0  5000.1     .16       0
Bank Sta=4996,5000.1
XS Rating Curve= 0 ,0
Exp/Cntr=0.3,0.1