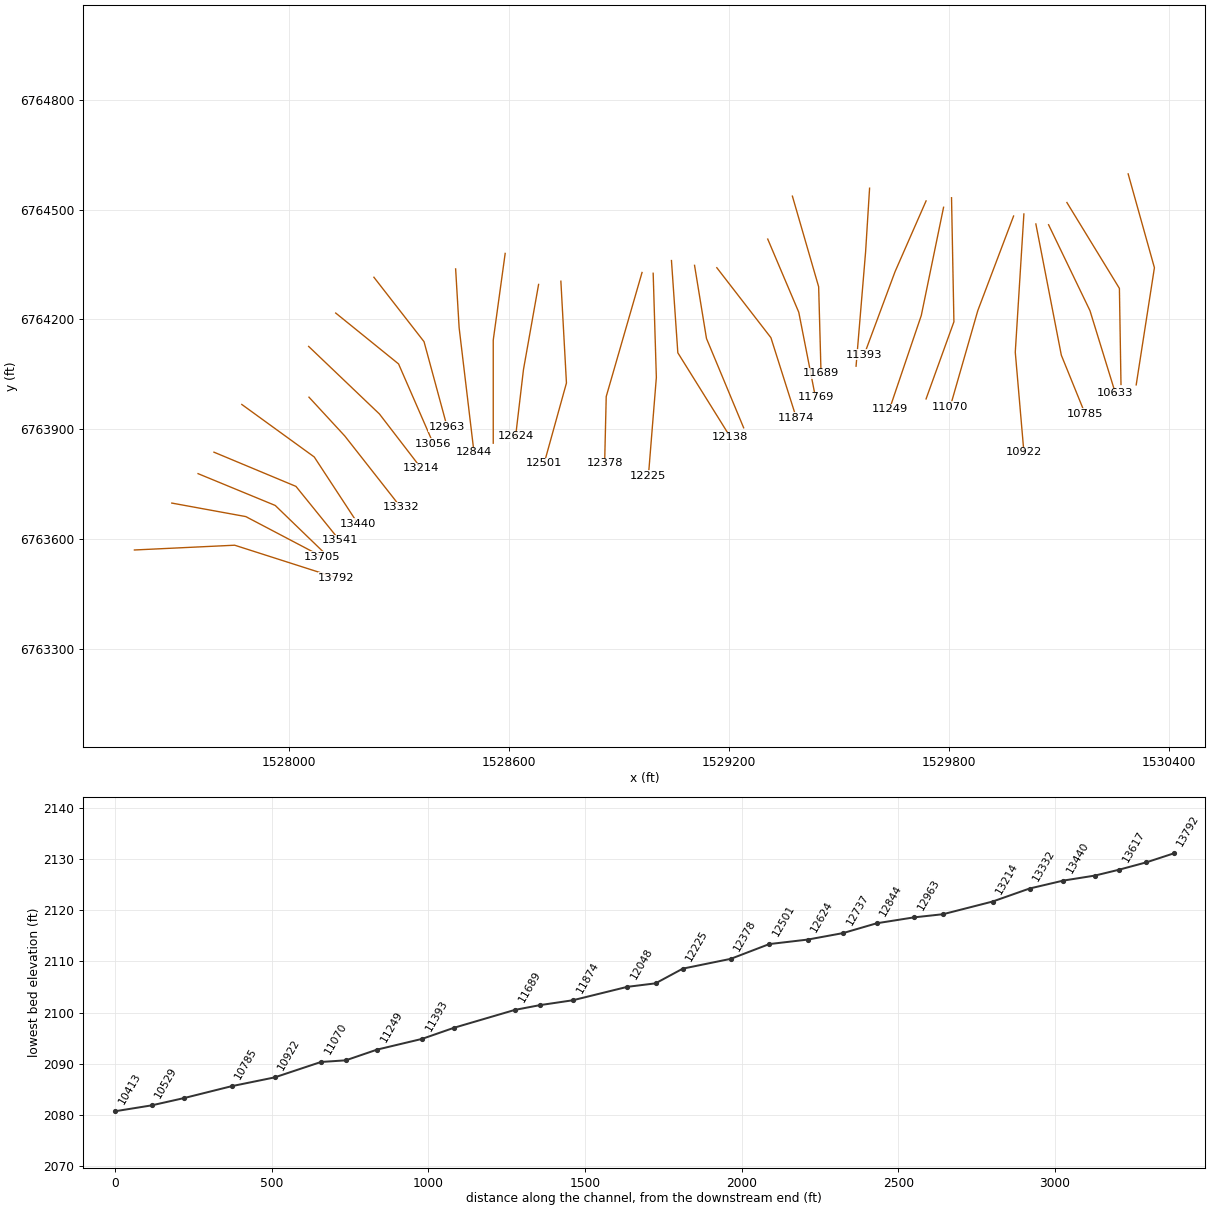
HEC-RAS study Elm 74.prj: Elm 74 Base Level Engineering

--- Elm 74.g01 (geometry) --- (continued)

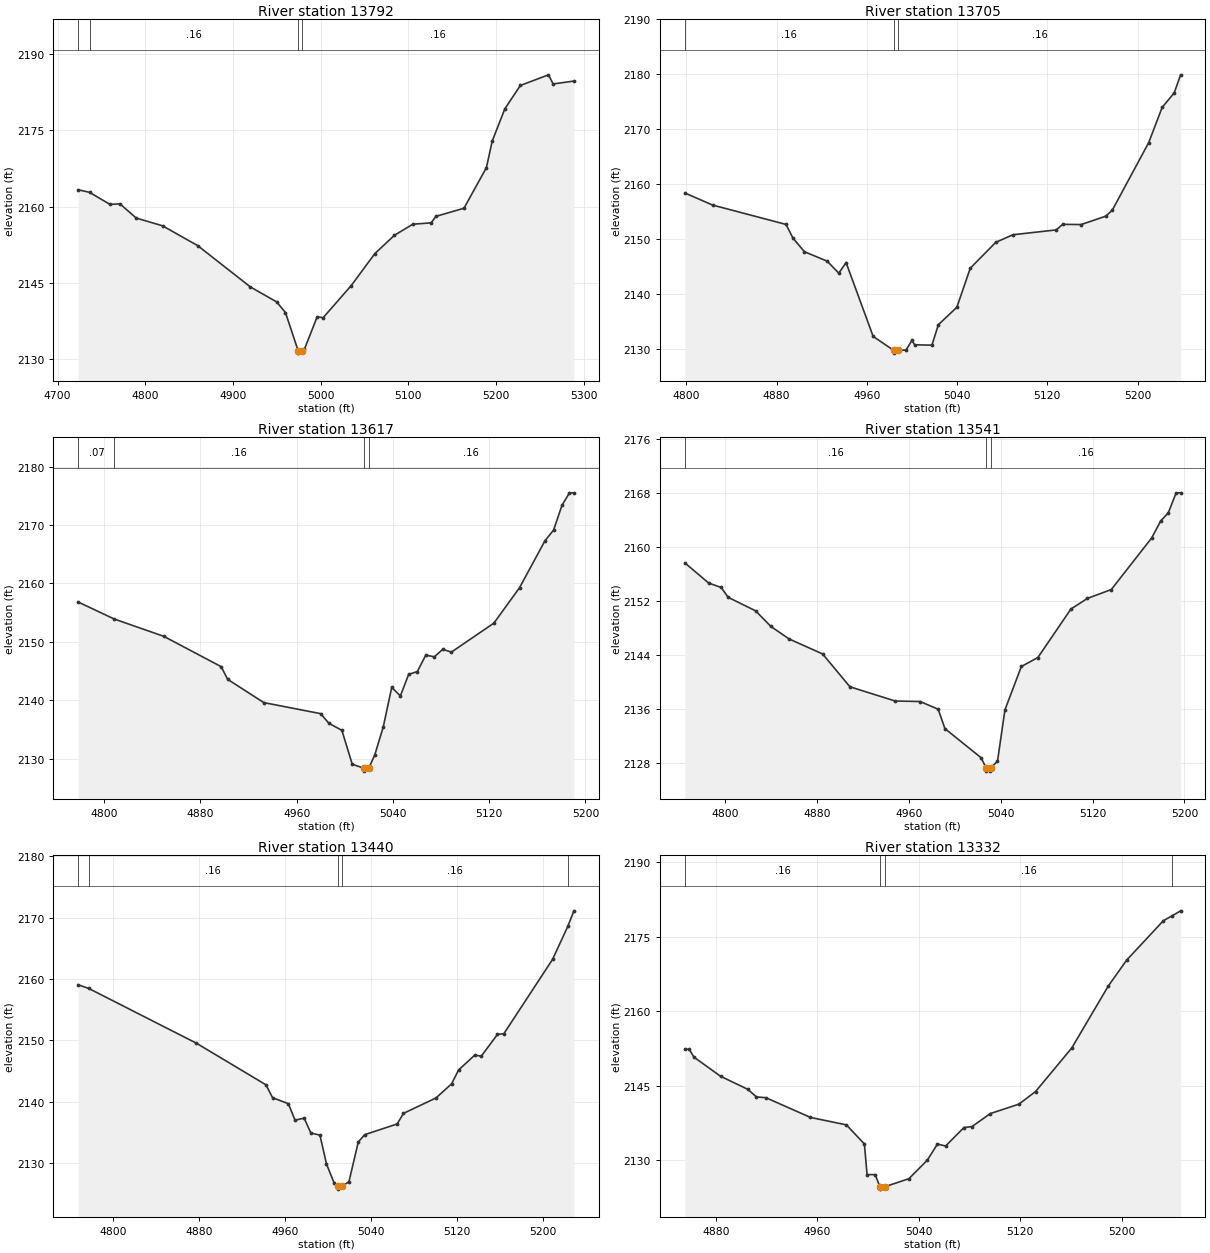
Type RM Length L Ch R = 1 ,13792   ,87,87,87
BEGIN DESCRIPTION:
Elm 74 13791.81
END DESCRIPTION:
XS GIS Cut Line= 3
      1527578.87       6763570.9      1527852.32      6763583.93
      1528130.06      6763494.96
#Sta/Elev= 30
  4723.4  2163.3  4736.3  2162.8  4759.6 2160.42    4771 2160.52  4789.6 2157.72
  4819.6 2156.19  4859.7 2152.28  4919.8 2144.13  4949.8 2141.17  4959.8 2139.08
  4974.2 2131.57  4974.4 2131.07  4978.3 2131.57  4981.3 2131.79    4996 2138.25
  5002.7 2138.05  5034.8  2144.4  5061.7  2150.7    5084 2154.31    5105  2156.5
    5126 2156.78  5131.3 2158.05  5163.4 2159.66    5189 2167.67  5195.6  2172.9
    5210 2179.27  5227.7 2183.88  5259.8 2185.98  5265.1 2184.18  5288.8 2184.75
#Mann= 4 ,-1 , 0
  4723.4     .07       0  4736.3     .16       0  4974.2     .07       0
  4978.3     .16       0
Bank Sta=4974.2,4978.3
XS Rating Curve= 0 ,0
Exp/Cntr=0.3,0.1

Type RM Length L Ch R = 1 ,13705   ,88,88,88
BEGIN DESCRIPTION:
Elm 74 13704.56
END DESCRIPTION:
XS GIS Cut Line= 3
      1527680.85      6763698.95       1527882.7      6763662.05
      1528090.09      6763553.01
#Sta/Elev= 30
  4798.7 2158.44  4823.2 2156.25  4888.4 2152.72  4894.4 2150.27  4904.6 2147.77
  4924.9 2146.04  4935.1 2143.87  4941.6 2145.78  4965.6 2132.37  4983.8 2129.83
  4984.1 2129.33  4987.9 2129.83  4994.8 2129.89  4999.9 2131.63  5002.5 2130.84
  5017.7 2130.78  5023.4 2134.49  5039.8 2137.67  5051.7 2144.77  5074.3 2149.47
  5089.5 2150.85  5127.9 2151.73  5133.6 2152.74    5150  2152.7    5172 2154.24
  5177.7 2155.35  5209.9  2167.6  5221.8 2173.99  5232.5 2176.64  5238.2 2179.92
#Mann= 3 ,-1 , 0
  4798.7     .16       0  4983.8     .07       0  4987.9     .16       0
Bank Sta=4983.8,4987.9
XS Rating Curve= 0 ,0
Exp/Cntr=0.3,0.1

Type RM Length L Ch R = 1 ,13617   ,76,76,76
BEGIN DESCRIPTION:
Elm 74 13617.29
END DESCRIPTION:
XS GIS Cut Line= 3
      1527752.46      6763779.25      1527962.99      6763692.43
      1528095.37       6763564.4
#Sta/Elev= 30
  4778.5 2156.82  4808.6  2153.9  4849.5 2150.96  4897.3 2145.76  4902.7 2143.59
  4932.7 2139.61  4979.9 2137.72  4986.8 2136.07  4997.6 2134.86  5006.2 2129.07
  5015.8 2128.38  5016.1 2127.88  5019.9 2128.38  5024.9 2130.63    5032 2135.47
    5039 2142.21  5046.2 2140.75  5053.1 2144.44  5060.3 2144.92  5067.3 2147.73
  5074.5 2147.45  5081.4 2148.73  5088.6 2148.25  5123.9 2153.21  5145.2 2159.27
  5166.3 2167.29  5173.5 2169.14  5180.5 2173.38  5186.7 2175.51  5190.4 2175.51
#Mann= 4 ,-1 , 0
  4778.5     .07       0  4808.6     .16       0  5015.8     .07       0
  5019.9     .16       0
Bank Sta=5015.8,5019.9
XS Rating Curve= 0 ,0
Exp/Cntr=0.3,0.1

Type RM Length L Ch R = 1 ,13541   ,101,101,101
BEGIN DESCRIPTION:
Elm 74 13540.52
END DESCRIPTION:
XS GIS Cut Line= 3
      1527795.88      6763837.84      1528019.42      6763744.52
      1528138.75      6763596.97
#Sta/Elev= 30
  4764.7 2157.61  4785.4 2154.63  4796.3 2153.97  4802.4 2152.51  4826.3 2150.51
  4839.6  2148.2  4855.5 2146.34  4884.7 2144.12  4908.5 2139.25    4948 2137.14
  4969.6 2137.07  4985.4 2135.93  4991.3 2133.05  5022.8 2128.74  5027.1 2127.25
  5027.4 2126.75    5031 2126.75  5031.2 2127.25  5037.1 2128.21  5043.6 2135.84
  5057.9 2142.26  5072.3 2143.59  5101.1 2150.78  5115.5 2152.35  5136.3 2153.67
  5171.5 2161.32  5179.4 2163.85  5185.9 2165.02  5192.8    2168  5196.7    2168
#Mann= 3 ,-1 , 0
  4764.7     .16       0  5027.1     .07       0  5031.2     .16       0
Bank Sta=5027.1,5031.2
XS Rating Curve= 0 ,0
Exp/Cntr=0.3,0.1

Type RM Length L Ch R = 1 ,13440   ,108,108,108
BEGIN DESCRIPTION:
Elm 74 13440.38
END DESCRIPTION:
XS GIS Cut Line= 3
      1527871.82      6763968.06      1528069.33      6763824.81
      1528188.54      6763642.75
#Sta/Elev= 30
  4767.3 2159.04    4777 2158.46  4877.2 2149.55  4942.1 2142.76  4948.3 2140.66
    4963 2139.68  4969.2    2137  4977.7 2137.33  4983.9 2134.92  4992.4 2134.56
  4998.5 2129.87  5005.5 2126.82  5009.2 2126.27  5009.5 2125.77  5013.3 2126.27
  5019.4 2126.97  5028.1 2133.44  5034.1 2134.64  5064.3 2136.38  5070.2 2138.11
  5100.5 2140.62    5115 2142.92  5121.5 2145.17  5136.6  2147.6  5142.6 2147.42
  5157.7 2150.96  5163.7 2151.09    5209 2163.18  5223.2 2168.56  5228.9 2171.09
#Mann= 5 ,-1 , 0
  4767.3     .07       0    4777     .16       0  5009.2     .07       0
  5013.3     .16       0  5223.2     .07       0
Bank Sta=5009.2,5013.3
XS Rating Curve= 0 ,0
Exp/Cntr=0.3,0.1

Type RM Length L Ch R = 1 ,13332   ,118,118,118
BEGIN DESCRIPTION:
Elm 74 13332.197
END DESCRIPTION:
XS GIS Cut Line= 3
        1528055.        6763988.       1528152.8       6763881.9
        1528305.        6763688.
#Sta/Elev= 30
  4855.7 2152.35  4859.1 2152.35  4862.8 2150.77  4883.8 2146.92  4905.3 2144.29
  4912.1 2142.76  4919.5 2142.61  4954.7 2138.64    4983 2137.14  4997.2  2133.3
  4999.3 2127.14  5005.7 2127.14  5009.4 2124.72  5009.7 2124.22  5013.5 2124.72
  5032.3 2126.32  5046.8 2130.05  5054.8 2133.29  5061.2 2132.89  5075.7 2136.61
    5082 2136.79  5096.5 2139.42    5119 2141.31  5132.1 2143.84  5160.6 2152.58
  5189.6 2165.12    5204 2170.29  5232.9 2178.21  5239.5 2179.15  5246.5 2180.19
#Mann= 4 ,-1 , 0
  4855.7     .16       0  5009.4     .07       0  5013.5     .16       0
  5239.5     .07       0
Bank Sta=5009.4,5013.5
XS Rating Curve= 0 ,0
Exp/Cntr=0.3,0.1

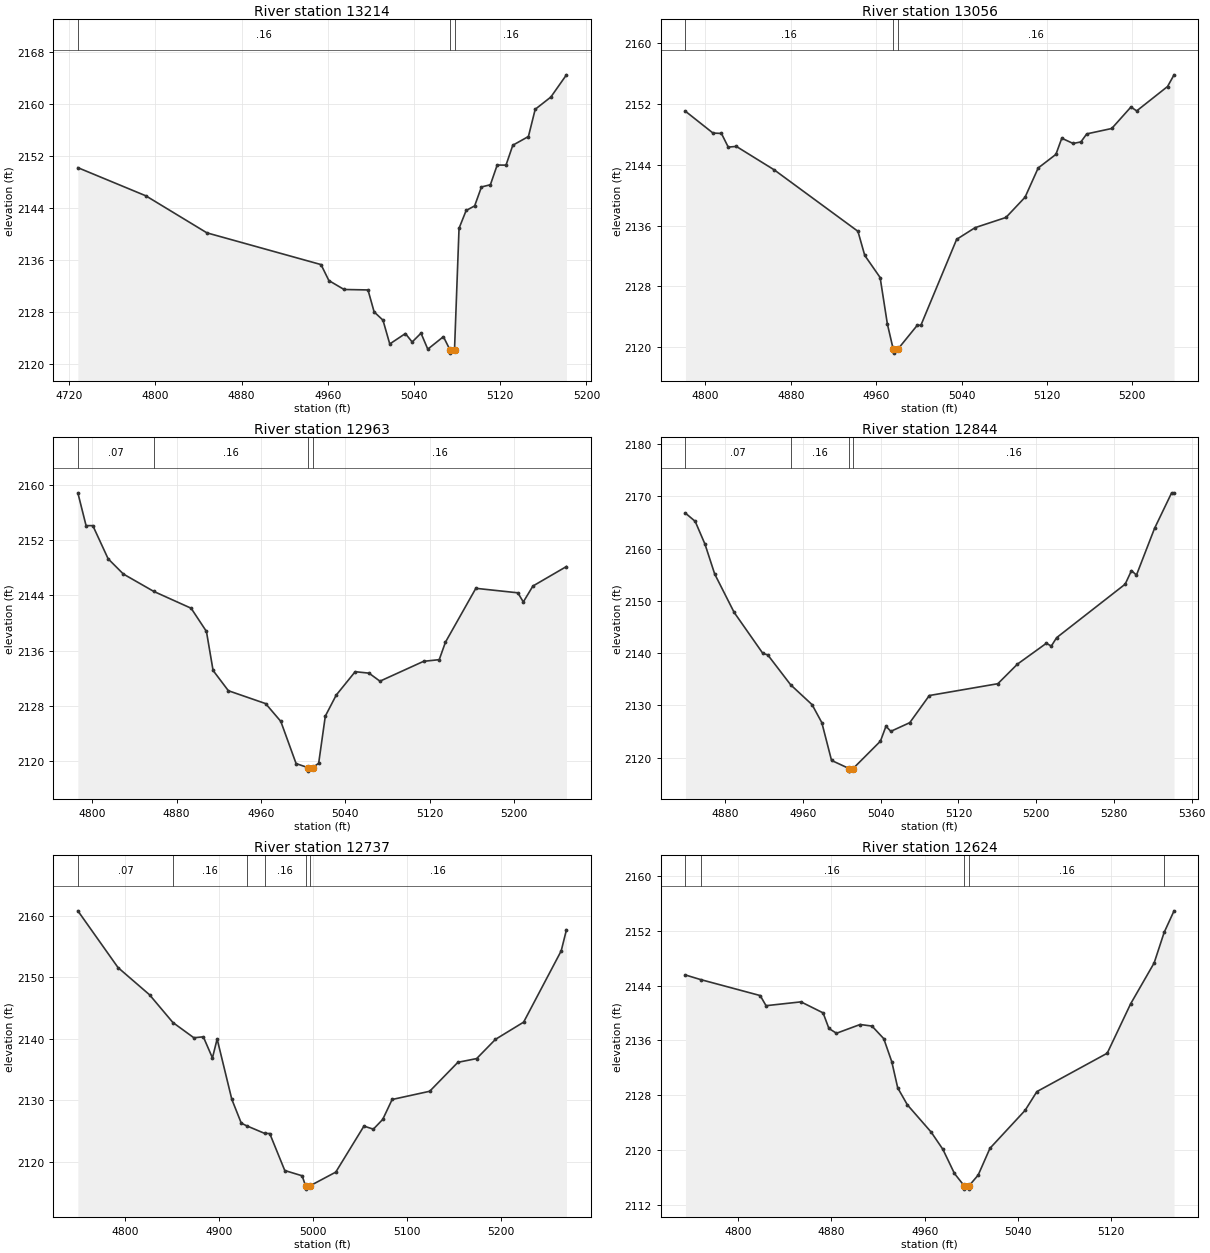
Type RM Length L Ch R = 1 ,13214   ,158,158,158
BEGIN DESCRIPTION:
Elm 74 13213.95
END DESCRIPTION:
XS GIS Cut Line= 3
      1528054.16      6764126.44      1528247.28        6763942.
      1528360.86      6763794.13
#Sta/Elev= 30
    4728 2150.21  4791.1 2145.88  4847.8 2140.18  4953.7  2135.3    4961 2132.84
  4975.1 2131.47  4997.3  2131.4    5003 2128.02  5011.2 2126.75  5017.5 2123.09
    5032 2124.69  5038.3 2123.39  5046.5 2124.75  5052.8 2122.29  5067.3 2124.21
  5073.4 2122.18  5073.7 2121.68  5077.6 2122.18  5081.8 2140.88  5088.4 2143.62
  5096.3 2144.33  5102.6 2147.24  5110.9 2147.58  5117.2 2150.61  5125.4  2150.6
  5131.7 2153.66  5146.2    2155  5152.5 2159.19    5167 2161.07  5181.5 2164.49
#Mann= 3 ,-1 , 0
    4728     .16       0  5073.4     .07       0  5077.6     .16       0
Bank Sta=5073.4,5077.6
XS Rating Curve= 0 ,0
Exp/Cntr=0.3,0.1

Type RM Length L Ch R = 1 ,13056   ,93,93,93
BEGIN DESCRIPTION:
Elm 74 13055.96
END DESCRIPTION:
XS GIS Cut Line= 3
      1528127.95      6764217.58      1528299.36      6764078.72
       1528394.1      6763861.26
#Sta/Elev= 30
  4781.3 2151.07  4807.1  2148.2    4815 2148.15  4821.4 2146.35    4829 2146.44
  4864.6 2143.34  4942.9 2135.26  4949.3 2132.08  4963.7 2129.17  4970.5 2123.04
    4976 2119.71  4976.3 2119.21  4980.2 2119.71  4998.5 2122.88  5001.9 2122.88
  5035.4  2134.2  5052.7 2135.74  5081.6 2137.08  5099.5 2139.75  5111.8  2143.6
  5128.4 2145.39  5133.9 2147.52  5144.5 2146.83  5151.8 2147.03  5157.3 2148.09
  5180.7  2148.8  5198.7 2151.63  5204.1 2151.12    5233 2154.33  5239.1 2155.87
#Mann= 3 ,-1 , 0
  4781.3     .16       0    4976     .07       0  4980.2     .16       0
Bank Sta=4976,4980.2
XS Rating Curve= 0 ,0
Exp/Cntr=0.3,0.1

Type RM Length L Ch R = 1 ,12963   ,119,119,119
BEGIN DESCRIPTION:
Elm 74 12962.56
END DESCRIPTION:
XS GIS Cut Line= 3
      1528232.11      6764315.24      1528368.81      6764139.48
      1528431.73      6763907.32
#Sta/Elev= 30
  4786.4 2158.81  4794.2 2154.07  4800.6 2154.07  4815.1 2149.28  4829.5 2147.08
  4858.4 2144.56  4893.8 2142.13  4908.3 2138.78  4914.6 2133.14  4929.1 2130.21
  4964.4 2128.35  4978.8 2125.78  4993.3 2119.68  5004.7 2119.09    5005 2118.59
  5008.9 2119.09  5014.7 2119.73    5021 2126.54  5031.3 2129.57  5049.3 2132.96
  5062.4 2132.75  5072.8 2131.59  5114.2 2134.46    5129  2134.7  5134.9 2137.23
  5163.7 2145.01  5203.5 2144.36  5208.7 2143.04  5217.8 2145.34  5249.6 2148.16
#Mann= 4 ,-1 , 0
  4786.4     .07       0  4858.4     .16       0  5004.7     .07       0
  5008.9     .16       0
Bank Sta=5004.7,5008.9
XS Rating Curve= 0 ,0
Exp/Cntr=0.3,0.1

Type RM Length L Ch R = 1 ,12844   ,107,107,107
BEGIN DESCRIPTION:
Elm 74 12843.982
END DESCRIPTION:
XS GIS Cut Line= 3
        1528455.      6764338.03      1528464.55      6764177.51
        1528505.      6763838.01
#Sta/Elev= 30
  4839.2 2166.78  4849.2 2165.22  4859.3 2160.85  4869.3 2155.14  4889.3  2147.8
  4918.9 2139.94  4923.9 2139.67  4947.5 2133.94  4969.5 2130.15  4979.5 2126.72
  4989.5 2119.49  5007.5 2117.94  5007.7 2117.44  5011.7 2117.94  5039.8 2123.17
  5045.5 2126.03  5050.5 2125.05    5070 2126.71  5090.1  2131.9  5160.6 2134.16
  5180.8 2137.91  5210.5 2141.89  5215.6 2141.36  5221.1 2142.97  5291.6  2153.2
  5298.1  2155.8  5303.2 2154.93  5321.8 2163.86  5339.4 2170.67  5341.9 2170.67
#Mann= 4 ,-1 , 0
  4839.2     .07       0  4947.5     .16       0  5007.5     .07       0
  5011.7     .16       0
Bank Sta=5007.5,5011.7
XS Rating Curve= 0 ,0
Exp/Cntr=0.3,0.1

Type RM Length L Ch R = 1 ,12737   ,113,113,113
BEGIN DESCRIPTION:
Elm 74 12737.04
END DESCRIPTION:
XS GIS Cut Line= 3
      1528590.16      6764380.37      1528557.61      6764143.82
      1528557.61       6763862.4
#Sta/Elev= 30
  4749.3 2160.83  4792.1 2151.59  4825.6 2147.17  4850.5 2142.65  4872.8 2140.17
  4882.9 2140.32  4892.6 2136.89  4897.6 2139.97  4913.2 2130.16  4923.3 2126.27
    4929 2125.84  4948.2  2124.6  4953.6 2124.58  4969.6 2118.56  4988.1  2117.7
  4991.8 2116.03    4992 2115.53    4996 2116.03  5023.9  2118.3  5053.9 2125.79
  5063.9 2125.29  5073.9 2126.88  5083.9 2130.12  5123.9 2131.46  5153.9 2136.17
  5173.9 2136.78  5193.9 2139.91  5223.9 2142.71  5263.9 2154.31  5269.5 2157.75
#Mann= 6 ,-1 , 0
  4749.3     .07       0  4850.5     .16       0    4929     .07       0
  4948.2     .16       0  4991.8     .07       0    4996     .16       0
Bank Sta=4991.8,4996
XS Rating Curve= 0 ,0
Exp/Cntr=0.3,0.1

Type RM Length L Ch R = 1 ,12624   ,123,123,123
BEGIN DESCRIPTION:
Elm 74 12624.28
END DESCRIPTION:
XS GIS Cut Line= 3
       1528681.3       6764295.7      1528640.08      6764063.53
       1528618.6      6763880.99
#Sta/Elev= 30
  4754.6 2145.57  4767.6  2144.9  4818.8 2142.56  4823.8 2141.08  4853.8 2141.64
  4872.8 2140.03  4877.8 2137.75  4884.3 2137.05  4904.6 2138.33  4914.8  2138.1
  4924.9 2136.26  4931.8 2132.88  4936.9 2129.06  4945.2 2126.58  4965.6  2122.6
  4975.7 2120.07  4985.6 2116.55  4993.9 2114.76  4994.2 2114.26  4997.9 2114.26
  4998.2 2114.76    5006 2116.32  5016.1 2120.23  5046.3 2125.78  5056.4 2128.52
  5116.8 2134.13  5136.9 2141.35  5157.1 2147.33  5165.7  2151.8  5174.2 2154.95
#Mann= 5 ,-1 , 0
  4754.6     .07       0  4767.6     .16       0  4993.9     .07       0
  4998.2     .16       0  5165.7     .07       0
Bank Sta=4993.9,4998.2
XS Rating Curve= 0 ,0
Exp/Cntr=0.3,0.1

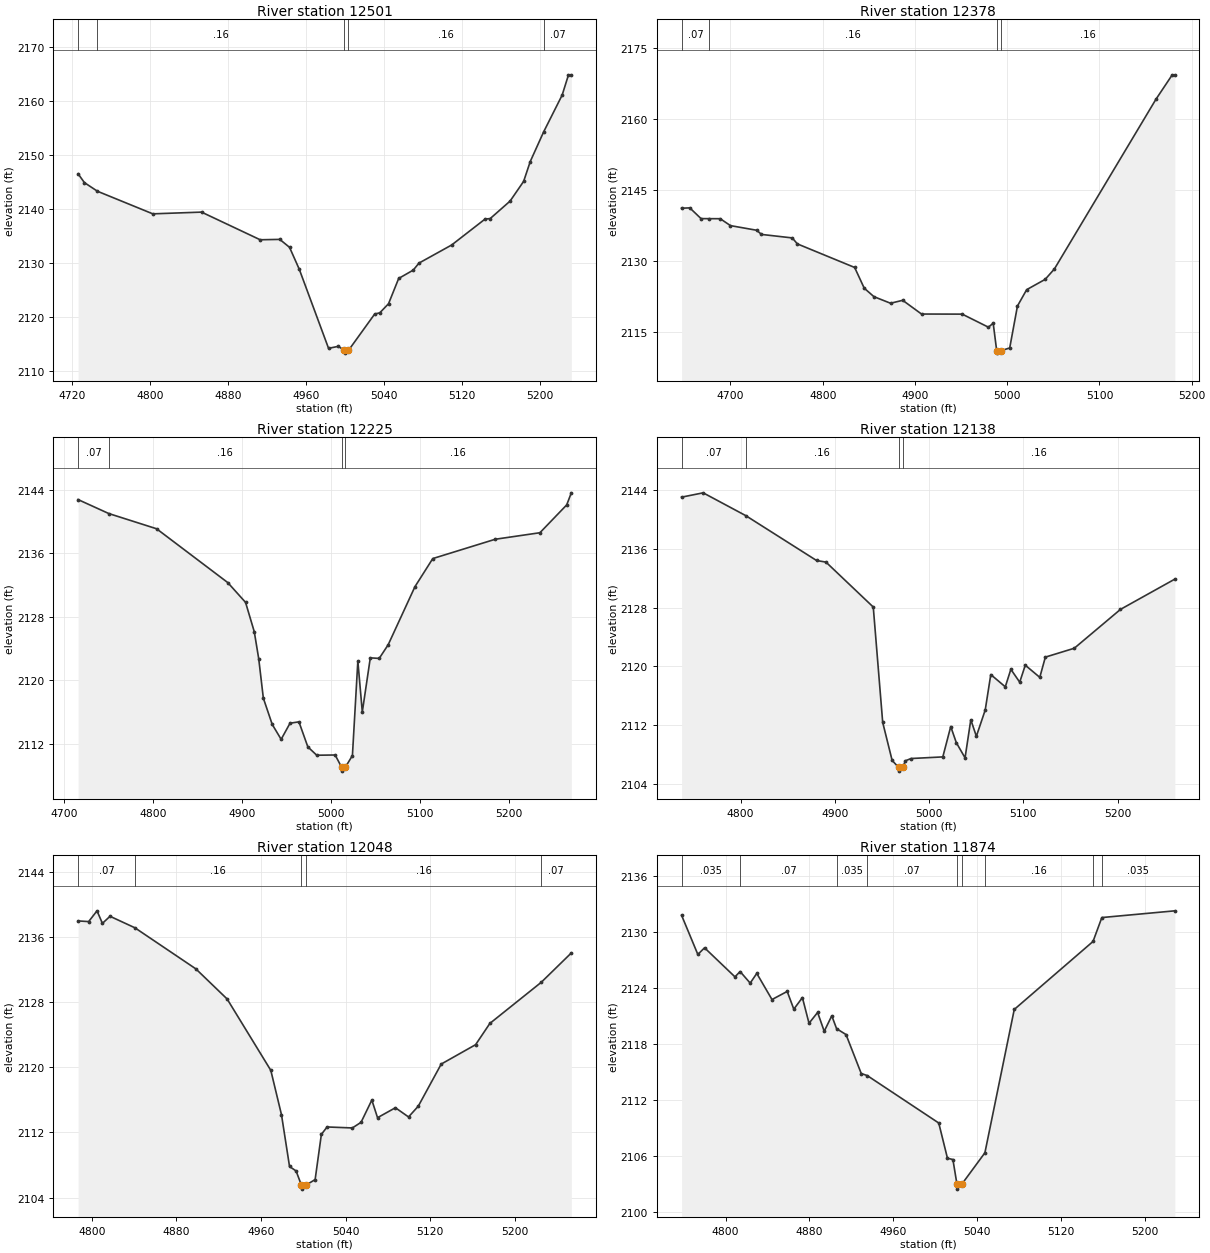
Type RM Length L Ch R = 1 ,12501   ,123,123,123
BEGIN DESCRIPTION:
Elm 74 12500.82
END DESCRIPTION:
XS GIS Cut Line= 3
      1528742.07      6764304.46      1528757.26      6764026.63
       1528696.5      6763807.44
#Sta/Elev= 30
  4726.4 2146.59  4732.9 2144.95  4746.3 2143.35    4803 2139.17    4853 2139.49
  4913.1 2134.37  4933.2 2134.44  4943.2 2132.97  4953.2  2128.9  4983.2 2114.27
  4993.3 2114.64  4999.3 2113.88  4999.6 2113.38  5003.6 2113.88  5030.5 2120.62
  5035.7 2120.84  5044.7 2122.53  5055.1 2127.21    5070 2128.75  5075.9 2130.05
  5109.4  2133.4  5143.7 2138.21  5148.9 2138.29  5169.3 2141.53  5183.2 2145.18
    5190 2148.86  5203.7 2154.34  5222.7 2161.16  5229.2 2164.91  5232.1 2164.91
#Mann= 5 ,-1 , 0
  4726.4     .07       0  4746.3     .16       0  4999.3     .07       0
  5003.6     .16       0  5203.7     .07       0
Bank Sta=4999.3,5003.6
XS Rating Curve= 0 ,0
Exp/Cntr=0.3,0.1

Type RM Length L Ch R = 1 ,12378   ,153,153,153
BEGIN DESCRIPTION:
Elm 74 12377.66
END DESCRIPTION:
XS GIS Cut Line= 3
      1528963.43      6764328.29      1528865.77      6763989.74
      1528861.43      6763807.44
#Sta/Elev= 30
    4647 2141.12  4655.9 2141.19  4668.1 2138.92  4676.8 2138.91  4688.9  2138.9
    4700 2137.44  4728.4 2136.46  4733.6 2135.58    4767 2134.84  4772.5 2133.58
  4834.6  2128.6    4845 2124.22  4855.5 2122.43  4873.5 2121.04  4886.7 2121.66
  4907.1 2118.76  4951.2 2118.74  4979.6 2115.98  4984.8 2116.82  4988.6    2111
  4988.9  2110.5  4992.9    2111  5002.7 2111.59  5011.1 2120.46  5021.1 2123.91
  5041.1 2126.08  5051.1 2128.27  5161.1  2164.1  5178.9  2169.3  5181.7  2169.3
#Mann= 4 ,-1 , 0
    4647     .07       0  4676.8     .16       0  4988.6     .07       0
  4992.9     .16       0
Bank Sta=4988.6,4992.9
XS Rating Curve= 0 ,0
Exp/Cntr=0.3,0.1

Type RM Length L Ch R = 1 ,12225   ,87,87,87
BEGIN DESCRIPTION:
Elm 74 12225.07
END DESCRIPTION:
XS GIS Cut Line= 3
      1528993.81      6764326.12      1529002.49      6764041.82
       1528980.8      6763772.82
#Sta/Elev= 30
  4715.9 2142.75  4750.5 2140.99  4804.1 2139.08  4884.1 2132.31  4904.1 2129.82
  4913.9 2126.13  4918.9 2122.73  4924.1 2117.77  4934.1 2114.46  4944.1 2112.59
  4954.1 2114.62  4964.1 2114.79  4974.1 2111.64  4984.1 2110.59  5004.8 2110.62
    5012 2109.09  5012.3 2108.59  5016.3 2109.09  5024.2 2110.55  5030.3 2122.44
  5035.3 2116.03  5044.3 2122.84  5054.3 2122.77  5064.4 2124.49  5094.5  2131.8
  5114.5 2135.33  5184.7 2137.76  5234.9 2138.58    5265 2142.08  5270.2  2143.6
#Mann= 4 ,-1 , 0
  4715.9     .07       0  4750.5     .16       0    5012     .07       0
  5016.3     .16       0
Bank Sta=5012,5016.3
XS Rating Curve= 0 ,0
Exp/Cntr=0.3,0.1

Type RM Length L Ch R = 1 ,12138   ,90,90,90
BEGIN DESCRIPTION:
Elm 74 12138.06
END DESCRIPTION:
XS GIS Cut Line= 3
      1529043.72      6764360.88      1529061.08       6764109.1
      1529204.33      6763879.03
#Sta/Elev= 30
  4737.3 2143.09  4760.2 2143.68  4805.4 2140.57  4880.5 2134.45  4890.5 2134.23
  4940.7  2128.1  4950.7 2112.37  4960.7 2107.19  4967.6 2106.22  4967.9 2105.72
    4972 2106.22  4974.8 2107.13  4980.8 2107.44  5014.5 2107.66  5022.9  2111.8
  5028.8 2109.61  5038.1 2107.53  5044.2 2112.73  5050.1 2110.47  5059.5 2114.06
  5065.4 2118.89  5080.8 2117.22  5086.7 2119.61  5096.1 2117.85    5102 2120.17
  5117.4 2118.51  5123.3 2121.27    5154 2122.48    5203 2127.78  5260.7 2131.91
#Mann= 4 ,-1 , 0
  4737.3     .07       0  4805.4     .16       0  4967.6     .07       0
    4972     .16       0
Bank Sta=4967.6,4972
XS Rating Curve= 0 ,0
Exp/Cntr=0.3,0.1

Type RM Length L Ch R = 1 ,12048   ,174,174,174
BEGIN DESCRIPTION:
Elm 74 12048.3
END DESCRIPTION:
XS GIS Cut Line= 3
      1529106.65      6764347.84      1529139.21      6764148.16
      1529240.59      6763904.42
#Sta/Elev= 30
  4787.1 2137.96  4797.1 2137.88    4805  2139.2  4810.1 2137.66  4817.3 2138.53
  4840.8 2137.12  4898.4 2132.08    4928 2128.38  4969.3 2119.62  4979.4 2114.17
    4987 2107.82  4993.2 2107.27  4998.2 2105.54  4998.5 2105.04  5002.6 2105.54
  5011.2 2106.21  5017.1 2111.76  5022.5 2112.67  5046.4 2112.55  5054.6 2113.24
  5064.8 2115.97  5070.2 2113.81  5087.1 2115.03  5099.5  2113.9  5108.7 2115.22
  5130.4 2120.39  5162.9 2122.77  5176.4 2125.38    5225 2130.43  5253.4 2134.03
#Mann= 5 ,-1 , 0
  4787.1     .07       0  4840.8     .16       0  4998.2     .07       0
  5002.6     .16       0    5225     .07       0
Bank Sta=4998.2,5002.6
XS Rating Curve= 0 ,0
Exp/Cntr=0.3,0.1

Type RM Length L Ch R = 1 ,11874   ,105,105,105
BEGIN DESCRIPTION:
Elm 74 11873.53
END DESCRIPTION:
XS GIS Cut Line= 3
      1529167.41      6764341.31      1529314.99      6764150.33
      1529384.14      6763932.08
#Sta/Elev= 30
  4758.1 2131.74  4773.6 2127.55    4780 2128.26    4809 2125.15  4813.9 2125.72
  4823.5 2124.48  4829.8 2125.52  4844.3 2122.72  4858.8 2123.59  4865.1 2121.69
  4873.3 2122.93  4879.6 2120.18  4887.8 2121.34  4894.1 2119.32  4901.3 2120.98
  4905.9  2119.6  4914.9 2118.97  4929.4  2114.8  4935.1 2114.58  5003.3  2109.5
  5011.6 2105.73  5016.8 2105.59  5020.7 2102.92    5021 2102.42  5025.1 2102.92
  5047.3 2106.31  5075.3 2121.66  5150.4 2128.94  5158.8  2131.5  5228.4 2132.22
#Mann= 9 ,-1 , 0
  4758.1    .035       0  4813.9     .07       0  4905.9    .035       0
  4935.1     .07       0  5020.7     .07       0  5025.1     .07       0
  5047.3     .16       0  5150.4     .07       0  5158.8    .035       0
Bank Sta=5020.7,5025.1
XS Rating Curve= 0 ,0
Exp/Cntr=0.3,0.1

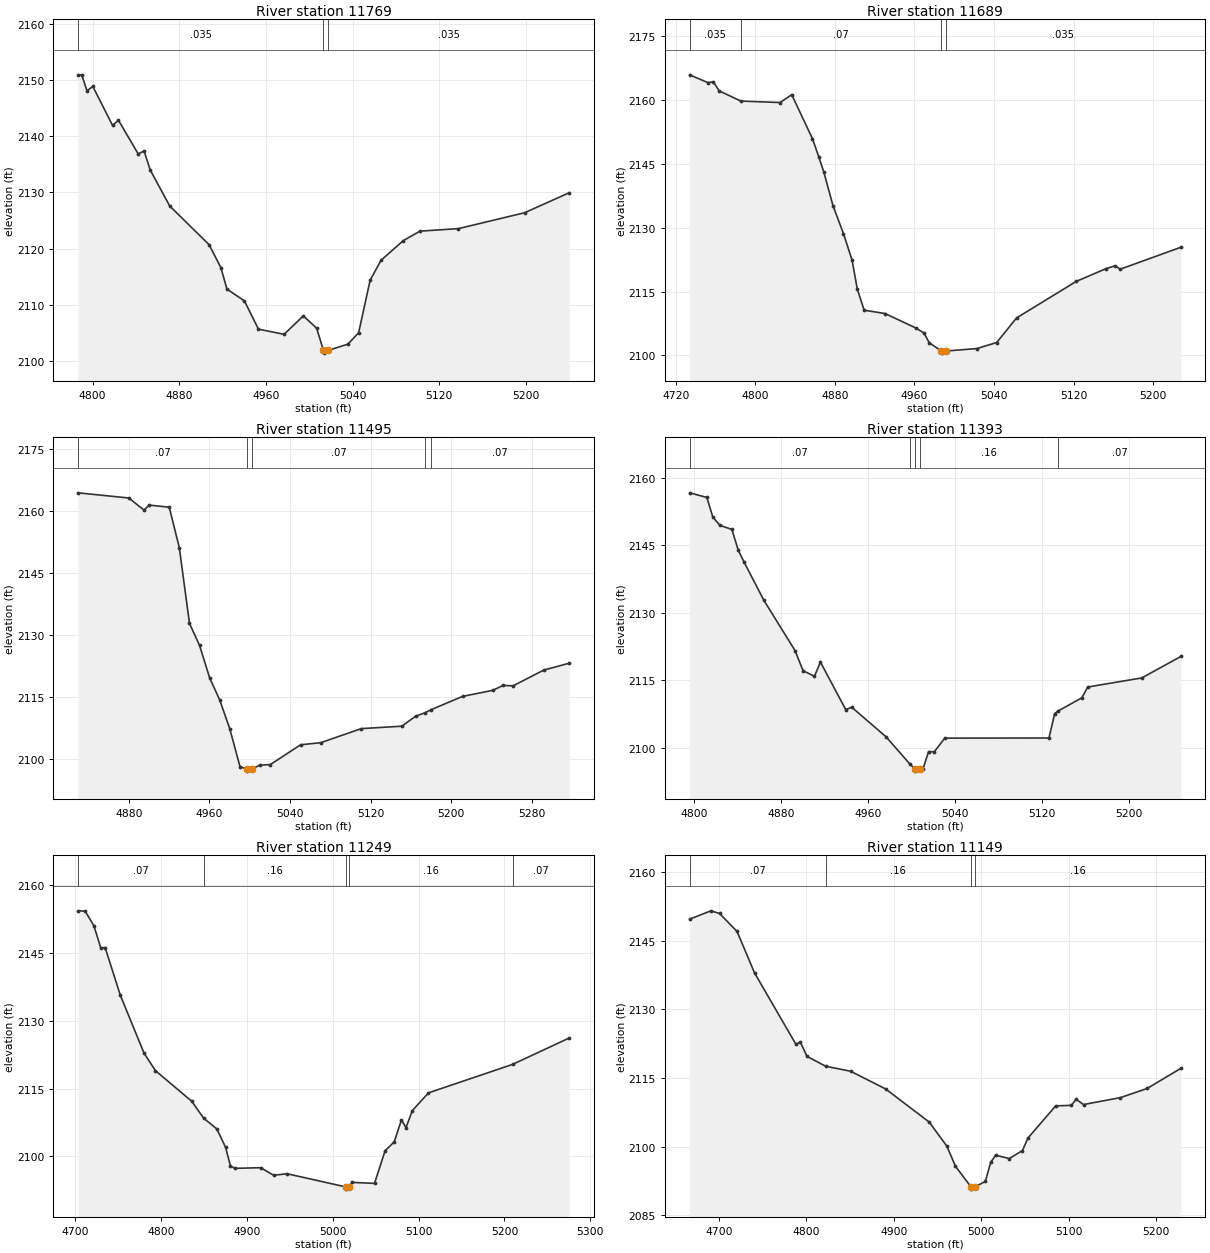
Type RM Length L Ch R = 1 ,11769   ,80,80,80
BEGIN DESCRIPTION:
Elm 74 11769.12
END DESCRIPTION:
XS GIS Cut Line= 3
      1529306.29      6764419.46      1529390.94      6764219.78
      1529436.51       6763987.6
#Sta/Elev= 30
  4786.5 2150.89    4790 2150.89  4794.8 2148.06  4800.2 2148.83  4818.4 2141.92
  4823.9 2142.81  4842.1 2136.84  4847.5 2137.36  4853.3 2133.95  4871.2  2127.6
  4907.6 2120.71  4918.4 2116.66    4924 2112.85  4940.2 2110.73  4953.1 2105.73
  4976.8 2104.81  4994.5 2108.08  5006.8 2105.91  5013.1 2101.97  5013.5 2101.47
  5017.6 2101.97  5035.8 2103.07  5045.6  2105.1  5056.2 2114.41  5066.3 2117.97
  5086.7 2121.43  5102.2 2123.13  5137.7 2123.58  5198.8  2126.4    5240 2129.95
#Mann= 3 ,-1 , 0
  4786.5    .035       0  5013.1    .035       0  5017.6    .035       0
Bank Sta=5013.1,5017.6
XS Rating Curve= 0 ,0
Exp/Cntr=0.3,0.1

Type RM Length L Ch R = 1 ,11689   ,194,194,194
BEGIN DESCRIPTION:
Elm 74 11688.68
END DESCRIPTION:
XS GIS Cut Line= 3
      1529373.58      6764536.61       1529445.2      6764289.22
       1529451.7      6764052.86
#Sta/Elev= 30
  4733.9 2165.93  4752.5 2164.08  4757.7 2164.31  4763.7 2162.15  4785.5 2159.76
  4824.9 2159.42  4836.6 2161.27  4857.4 2150.95  4863.7 2146.74  4868.9 2143.06
  4878.2 2135.09  4888.6 2128.64  4897.3 2122.38  4902.5 2115.61  4909.4 2110.63
  4930.3 2109.85  4961.5 2106.44  4969.7 2105.24  4974.9 2102.96  4987.2 2101.04
  4987.6 2100.54  4991.7 2101.04  5022.7 2101.61  5042.7 2103.03  5062.7 2108.81
  5122.7 2117.39  5152.7  2120.4  5161.9 2121.06  5166.9 2120.26  5227.9 2125.41
#Mann= 4 ,-1 , 0
  4733.9    .035       0  4785.5     .07       0  4987.2    .035       0
  4991.7    .035       0
Bank Sta=4987.2,4991.7
XS Rating Curve= 0 ,0
Exp/Cntr=0.3,0.1

Type RM Length L Ch R = 1 ,11495   ,102,102,102
BEGIN DESCRIPTION:
Elm 74 11494.73
END DESCRIPTION:
XS GIS Cut Line= 3
      1529584.09      6764558.34      1529573.24      6764384.71
      1529547.22      6764072.56
#Sta/Elev= 30
  4829.7 2164.37  4880.1 2163.12  4895.2 2160.19  4900.2  2161.4  4920.2  2160.9
  4930.2 2151.11  4940.3 2132.78  4950.3 2127.45  4960.3 2119.61  4970.3 2114.26
  4980.3 2107.26  4990.4 2098.13  4997.3 2097.56  4997.6 2097.06  5001.8 2097.56
  5010.4 2098.53  5020.4 2098.63  5050.5 2103.43  5070.6 2103.95  5110.7 2107.34
  5150.9 2107.93  5164.5 2110.34  5174.1  2111.2    5180 2111.93  5211.1 2115.13
  5241.2 2116.61  5251.2 2117.78  5261.3 2117.69  5291.4 2121.48  5316.9 2123.16
#Mann= 5 ,-1 , 0
  4829.7     .07       0  4997.3     .07       0  5001.8     .07       0
  5174.1     .16       0    5180     .07       0
Bank Sta=4997.3,5001.8
XS Rating Curve= 0 ,0
Exp/Cntr=0.3,0.1

Type RM Length L Ch R = 1 ,11393   ,144,144,144
BEGIN DESCRIPTION:
Elm 74 11392.81
END DESCRIPTION:
XS GIS Cut Line= 3
      1529738.16      6764523.59      1529653.53      6764330.45
      1529569.54      6764104.31
#Sta/Elev= 30
  4795.8 2156.63  4811.7  2155.6  4817.2 2151.23  4823.7 2149.42  4834.7 2148.51
  4840.6 2143.89    4846 2141.24    4864 2132.85  4892.8 2121.64  4900.2 2117.18
  4910.7 2115.93  4916.2 2119.08  4939.5 2108.53    4945 2109.07  4976.6  2102.5
  4998.4  2096.5    5003 2095.39  5003.4 2094.89  5007.5 2095.39  5010.6 2095.39
  5015.7 2099.21    5021 2099.19  5030.6 2102.21  5126.5 2102.24  5131.8 2107.63
  5134.8 2108.21  5156.8 2111.16  5162.2 2113.55    5212 2115.57  5247.9 2120.33
#Mann= 5 ,-1 , 0
  4795.8     .07       0  4998.4     .16       0    5003     .07       0
  5007.5     .16       0  5134.8     .07       0
Bank Sta=5003,5007.5
XS Rating Curve= 0 ,0
Exp/Cntr=0.3,0.1

Type RM Length L Ch R = 1 ,11249   ,100,100,100
BEGIN DESCRIPTION:
Elm 74 11248.77
END DESCRIPTION:
XS GIS Cut Line= 3
      1529785.91      6764506.26      1529725.15       6764211.1
      1529638.35      6763955.06
#Sta/Elev= 30
  4703.7 2154.22  4712.1 2154.15  4722.3 2150.89  4730.2 2146.05  4735.3 2146.11
    4753 2135.57  4780.6  2122.8  4793.8 2118.95    4836  2112.2    4850 2108.44
  4865.3 2106.07  4875.5 2102.01  4881.2 2097.88  4886.3 2097.38  4916.3 2097.52
  4931.5 2095.84    4947 2096.19  5015.1 2093.29  5015.4 2092.79  5019.6 2093.29
  5022.6 2094.28  5048.8 2094.06  5061.1 2101.26  5071.7 2103.21  5080.2 2108.08
  5085.4 2106.34  5092.8 2110.12  5111.6 2114.04  5209.6 2120.33  5275.4 2126.15
#Mann= 5 ,-1 , 0
  4703.7     .07       0    4850     .16       0  5015.1     .07       0
  5019.6     .16       0  5209.6     .07       0
Bank Sta=5015.1,5019.6
XS Rating Curve= 0 ,0
Exp/Cntr=0.3,0.1

Type RM Length L Ch R = 1 ,11149   ,79,79,79
BEGIN DESCRIPTION:
Elm 74 11149.18
END DESCRIPTION:
XS GIS Cut Line= 3
      1529807.61       6764532.3      1529814.12      6764193.73
      1529738.17      6763983.24
#Sta/Elev= 30
  4666.2 2149.73  4690.5 2151.56  4700.5 2150.98  4720.5 2147.06  4740.5    2138
    4788 2122.34    4793 2122.87  4800.5 2119.74  4821.9 2117.58  4850.5 2116.48
  4890.5 2112.62  4940.5 2105.37  4960.6 2100.13  4970.6  2095.7  4988.3  2091.2
  4988.6  2090.7  4992.8  2091.2  5004.8 2092.38  5010.9 2096.56  5016.6 2098.11
  5032.2 2097.39  5047.3 2099.13  5053.4 2101.83  5085.3 2108.91  5103.3 2109.02
  5108.6 2110.35  5117.2  2109.2  5159.4 2110.71    5190 2112.71  5228.6 2117.12
#Mann= 4 ,-1 , 0
  4666.2     .07       0  4821.9     .16       0  4988.3     .07       0
  4992.8     .16       0
Bank Sta=4988.3,4992.8
XS Rating Curve= 0 ,0
Exp/Cntr=0.3,0.1

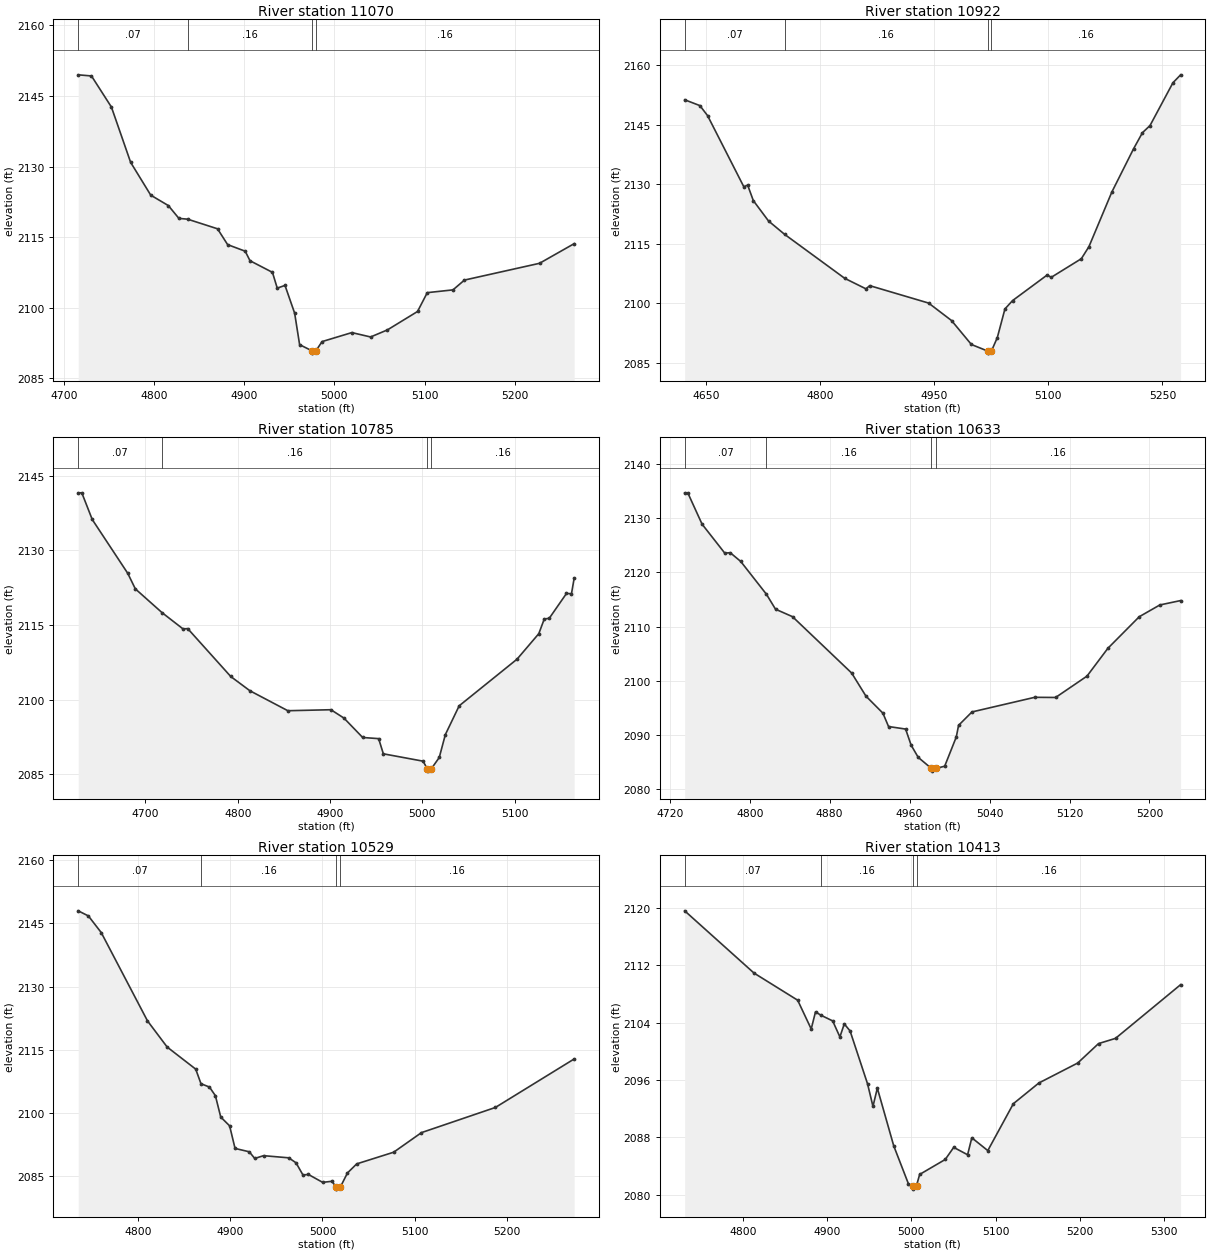
Type RM Length L Ch R = 1 ,11070   ,148,148,148
BEGIN DESCRIPTION:
Elm 74 11070.42
END DESCRIPTION:
XS GIS Cut Line= 3
      1529976.89      6764482.38      1529879.23      6764224.12
      1529803.78      6763961.13
#Sta/Elev= 30
  4716.1 2149.47  4730.8 2149.23  4752.9 2142.63  4774.2 2130.89  4796.5 2123.92
    4816 2121.71  4827.7 2118.99  4837.4 2118.82  4870.5 2116.78  4881.7 2113.42
  4901.2 2112.02  4906.5    2110  4931.4 2107.53  4936.7 2104.18  4945.3 2104.76
    4956 2098.86  4961.5 2092.18  4975.1 2090.88  4975.4 2090.38  4979.6 2090.88
  4986.4 2092.83  5019.4 2094.74  5040.2 2093.81  5058.9 2095.32  5092.2 2099.22
    5103 2103.22  5131.5 2103.81  5144.2 2105.89  5227.4 2109.45  5265.8 2113.62
#Mann= 4 ,-1 , 0
  4716.1     .07       0  4837.4     .16       0  4975.1     .07       0
  4979.6     .16       0
Bank Sta=4975.1,4979.6
XS Rating Curve= 0 ,0
Exp/Cntr=0.3,0.1

Type RM Length L Ch R = 1 ,10922   ,137,137,137
BEGIN DESCRIPTION:
Elm 74 10921.791
END DESCRIPTION:
XS GIS Cut Line= 3
        1530005.      6764488.01      1529981.48      6764110.84
        1530005.      6763837.96
#Sta/Elev= 30
  4622.1 2151.24  4642.1 2149.77  4652.2 2147.24  4699.8 2129.32  4704.9 2129.71
  4712.3 2125.83  4732.3 2120.68  4753.4 2117.32  4832.5 2106.22  4860.3 2103.58
  4865.3 2104.38  4942.7 2099.99  4972.8 2095.59  4998.9 2089.55  5020.6 2087.87
    5021 2087.37  5025.2 2087.87    5033 2091.29    5043 2098.51    5053 2100.61
  5098.7 2107.09  5103.7 2106.46  5143.4 2111.17  5153.4 2114.21  5183.5 2127.98
  5212.1  2138.9  5223.7 2142.93  5233.7 2144.75  5263.8 2155.53  5273.9 2157.53
#Mann= 4 ,-1 , 0
  4622.1     .07       0  4753.4     .16       0  5020.6     .07       0
  5025.2     .16       0
Bank Sta=5020.6,5025.2
XS Rating Curve= 0 ,0
Exp/Cntr=0.3,0.1

Type RM Length L Ch R = 1 ,10785   ,152,152,152
BEGIN DESCRIPTION:
Elm 74 10784.9
END DESCRIPTION:
XS GIS Cut Line= 3
      1530037.64       6764460.7      1530107.09      6764102.59
      1530171.98      6763942.53
#Sta/Elev= 30
  4627.1 2141.59    4631 2141.59  4642.3 2136.23  4680.8 2125.41    4689 2122.29
  4717.9 2117.52  4740.7 2114.24  4745.8  2114.3  4792.4 2104.68  4813.2 2101.81
  4854.3  2097.8    4901    2098  4915.1 2096.32  4935.4 2092.42  4952.7 2092.19
  4957.8 2089.14  5000.9 2087.66  5005.3 2086.16  5005.7 2085.66  5009.9 2086.16
  5018.4  2088.4    5025    2093    5040 2098.79  5102.7 2108.16  5126.3 2113.29
  5132.2 2116.23  5137.6 2116.37  5156.3 2121.37  5161.7 2121.31  5164.6 2124.42
#Mann= 4 ,-1 , 0
  4627.1     .07       0  4717.9     .16       0  5005.3     .07       0
  5009.9     .16       0
Bank Sta=5005.3,5009.9
XS Rating Curve= 0 ,0
Exp/Cntr=0.3,0.1

Type RM Length L Ch R = 1 ,10633   ,104,104,104
BEGIN DESCRIPTION:
Elm 74 10633.15
END DESCRIPTION:
XS GIS Cut Line= 3
      1530072.35      6764458.53      1530185.21      6764224.12
      1530254.66      6763998.43
#Sta/Elev= 30
  4734.9 2134.69    4738 2134.69  4752.3 2128.91    4775 2123.57  4780.5 2123.64
    4791 2122.03  4816.7 2115.98  4825.8 2113.22  4842.8 2111.84    4902 2101.44
  4916.3 2097.18  4933.3 2094.03  4938.9 2091.57    4956  2091.1  4961.5 2088.14
  4968.6 2085.88  4981.8 2083.84  4982.2 2083.34  4986.4 2083.84  4995.1 2084.25
  5006.7 2089.64    5009 2091.79  5022.4 2094.26  5085.2 2096.96  5106.1 2096.93
  5137.5 2100.87  5158.4    2106  5189.8 2111.83  5210.4    2114  5231.2 2114.81
#Mann= 4 ,-1 , 0
  4734.9     .07       0  4816.7     .16       0  4981.8     .07       0
  4986.4     .16       0
Bank Sta=4981.8,4986.4
XS Rating Curve= 0 ,0
Exp/Cntr=0.3,0.1

Type RM Length L Ch R = 1 ,10529   ,116,116,116
BEGIN DESCRIPTION:
Elm 74 10528.69
END DESCRIPTION:
XS GIS Cut Line= 3
      1530122.29      6764519.24      1530265.51      6764284.88
      1530269.84      6764022.67
#Sta/Elev= 30
  4735.6 2147.96  4746.6 2146.75  4760.5 2142.81  4810.6 2121.84  4831.9 2115.63
  4862.8 2110.39  4868.5 2106.93  4877.7 2106.13  4884.1 2104.09  4889.9 2099.02
  4899.5 2096.93  4905.4 2091.57  4920.8 2090.77  4926.7 2089.19  4936.3 2089.85
  4963.5 2089.34  4971.4 2088.16  4978.9 2085.27  4984.8 2085.39  5000.2 2083.52
  5010.3 2083.77  5014.8 2082.41  5015.2 2081.91  5019.4 2082.41  5027.1 2085.75
  5037.1  2087.9  5077.1 2090.67  5107.2 2095.32  5187.2 2101.29  5272.5  2112.8
#Mann= 4 ,-1 , 0
  4735.6     .07       0  4868.5     .16       0  5014.8     .07       0
  5019.4     .16       0
Bank Sta=5014.8,5019.4
XS Rating Curve= 0 ,0
Exp/Cntr=0.3,0.1

Type RM Length L Ch R = 1 ,10413   ,153,153,153
BEGIN DESCRIPTION:
Elm 74 10412.52
END DESCRIPTION:
XS GIS Cut Line= 3
      1530289.39      6764597.36        1530361.       6764341.3
       1530311.3      6764021.53
#Sta/Elev= 30
  4730.5 2119.63  4812.9 2110.94  4864.8 2107.15  4880.9 2103.13    4886 2105.52
  4892.5 2105.05  4906.4 2104.26    4915 2102.02  4920.2 2103.84  4927.1 2102.86
  4947.9 2095.46  4954.3 2092.32  4959.5 2094.87    4979 2086.81  4996.4 2081.53
  5001.5 2081.27  5001.9 2080.77  5006.1 2081.27  5009.8 2082.82  5040.2 2084.91
  5050.3  2086.6  5066.8 2085.57  5071.8 2087.94  5090.8 2086.15  5121.2  2092.7
  5151.5 2095.59  5197.7 2098.38  5222.4 2101.09  5242.6 2101.82    5320 2109.32
#Mann= 4 ,-1 , 0
  4730.5     .07       0  4892.5     .16       0  5001.5     .07       0
  5006.1     .16       0
Bank Sta=5001.5,5006.1
XS Rating Curve= 0 ,0
Exp/Cntr=0.3,0.1