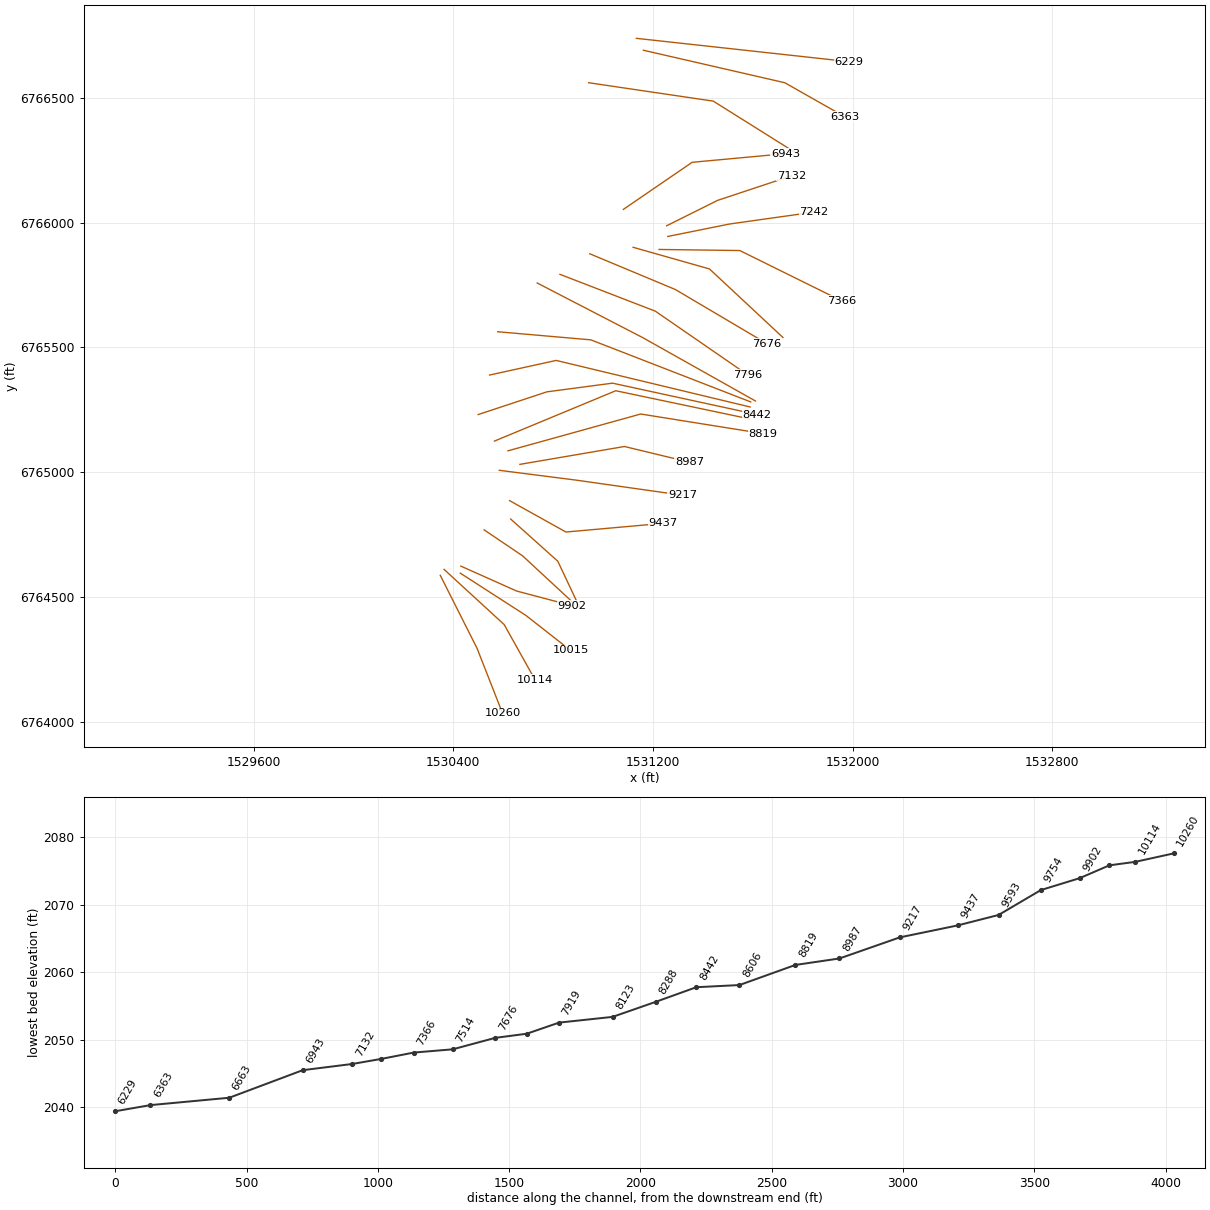
HEC-RAS study Elm 74.prj: Elm 74 Base Level Engineering

--- Elm 74.g01 (geometry) --- (continued)

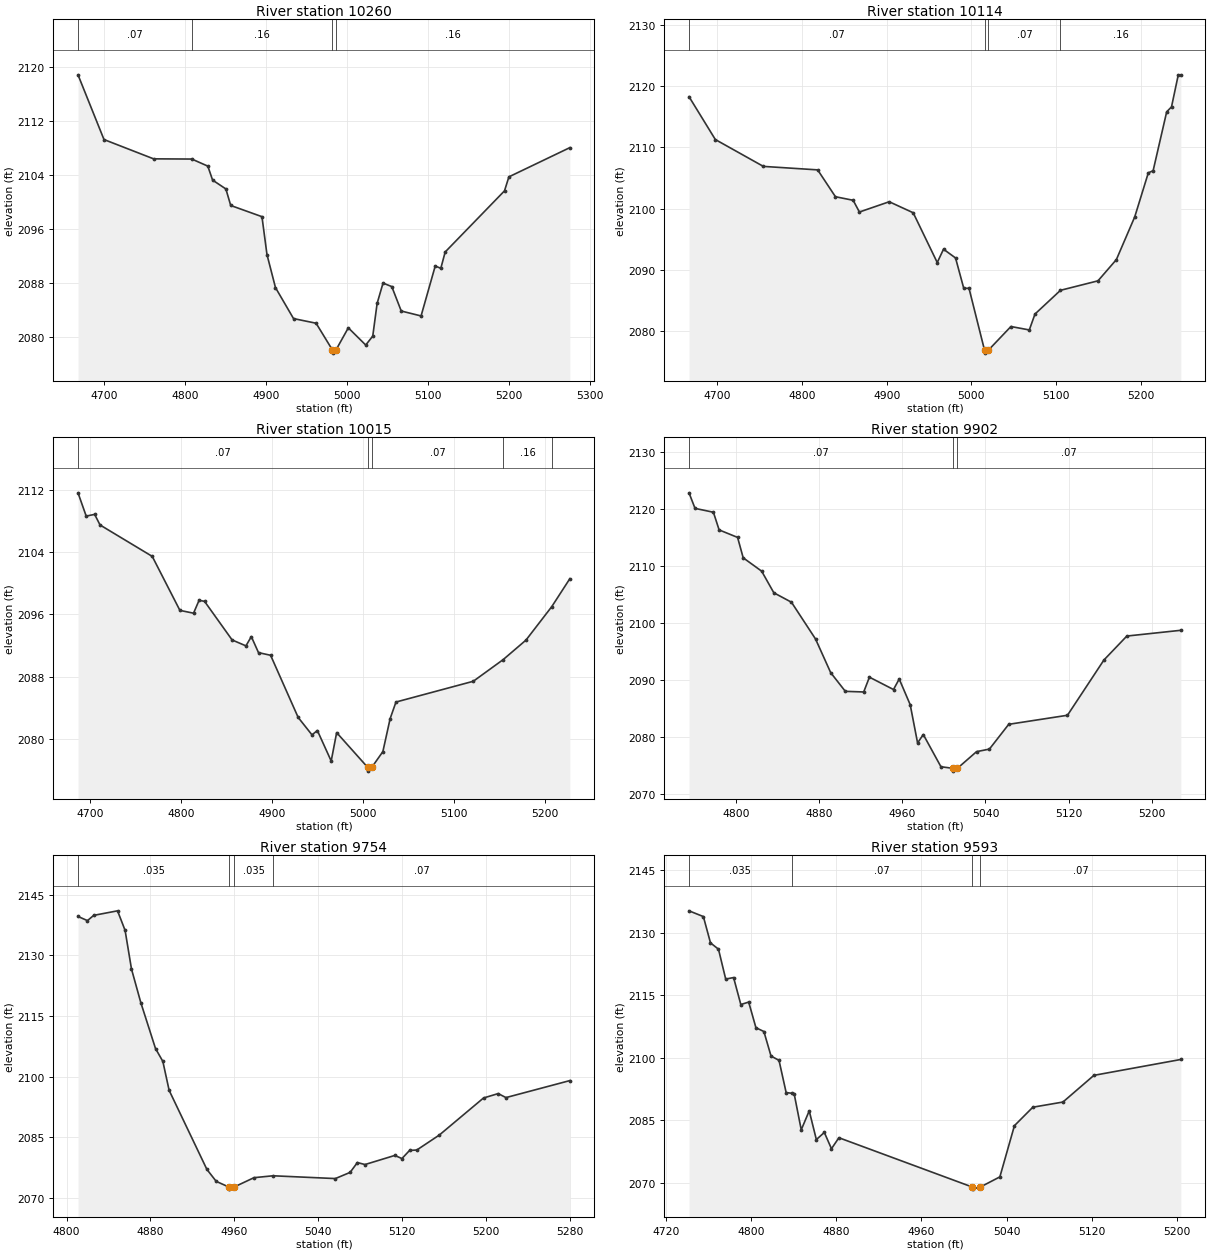
Type RM Length L Ch R = 1 ,10260   ,146,146,146
BEGIN DESCRIPTION:
Elm 74 10259.79
END DESCRIPTION:
XS GIS Cut Line= 3
      1530347.99       6764586.5      1530495.54      6764293.56
      1530597.55      6764033.12
#Sta/Elev= 30
  4667.7 2118.85  4699.8 2109.26  4761.1  2106.4  4808.3 2106.37  4828.1 2105.32
    4834 2103.25  4850.4 2101.94  4856.4 2099.49    4895 2097.83  4901.2 2092.21
  4911.7 2087.32    4934 2082.73  4961.9 2082.04  4981.9 2078.11  4982.3 2077.61
  4986.6 2078.11  5001.7 2081.36  5023.2 2078.81  5031.9 2080.13  5037.3 2084.98
  5044.6 2087.99  5055.4 2087.47  5067.1 2083.85  5091.6 2083.12  5109.1 2090.52
    5116 2090.18  5121.4  2092.6  5194.7 2101.66  5200.1 2103.73  5275.4 2108.06
#Mann= 4 ,-1 , 0
  4667.7     .07       0  4808.3     .16       0  4981.9     .07       0
  4986.6     .16       0
Bank Sta=4981.9,4986.6
XS Rating Curve= 0 ,0
Exp/Cntr=0.3,0.1

Type RM Length L Ch R = 1 ,10114   ,99,99,99
BEGIN DESCRIPTION:
Elm 74 10113.75
END DESCRIPTION:
XS GIS Cut Line= 3
      1530363.17       6764610.4      1530604.05      6764389.05
      1530727.74       6764167.7
#Sta/Elev= 30
  4666.6 2118.29  4697.7 2111.28  4754.4 2106.89  4818.5 2106.32  4839.5 2101.93
  4860.4 2101.35  4867.8 2099.43    4903 2101.11  4931.3 2099.31  4959.7 2091.17
  4967.1 2093.35  4981.3 2091.92    4991 2086.96  4997.2 2086.96  5015.5 2076.86
  5015.9 2076.36  5020.2 2076.86  5046.7 2080.71  5068.4 2080.15  5075.1 2082.75
  5105.2 2086.63  5149.5 2088.18  5171.2 2091.65  5192.9 2098.64  5208.9 2105.83
  5214.6 2106.19  5230.6 2115.81  5236.3 2116.62  5244.3 2121.86  5247.3 2121.86
#Mann= 4 ,-1 , 0
  4666.6     .07       0  5015.5     .07       0  5020.2     .07       0
  5105.2     .16       0
Bank Sta=5015.5,5020.2
XS Rating Curve= 0 ,0
Exp/Cntr=0.3,0.1

Type RM Length L Ch R = 1 ,10015   ,113,113,113
BEGIN DESCRIPTION:
Elm 74 10015.38
END DESCRIPTION:
XS GIS Cut Line= 3
      1530428.27      6764595.21      1530690.86      6764425.94
       1530870.5      6764285.25
#Sta/Elev= 30
  4686.3 2111.61  4695.3 2108.62  4704.6 2108.84  4710.5 2107.48  4767.9 2103.44
  4798.3  2096.5  4813.3 2096.14  4819.4  2097.8  4825.4 2097.66  4855.7  2092.7
  4870.9 2091.94  4876.8 2093.13  4884.7 2091.07    4898 2090.73  4928.3 2082.74
  4943.5  2080.5  4949.4 2081.06  4964.6 2077.14  4970.6 2080.79  5004.6 2076.34
  5004.9 2075.84  5009.3 2076.34  5021.4 2078.35  5029.4 2082.59  5035.8 2084.72
  5120.8 2087.39  5153.6 2090.17  5178.7 2092.68  5207.1 2096.99  5226.9 2100.57
#Mann= 5 ,-1 , 0
  4686.3     .07       0  5004.6     .07       0  5009.3     .07       0
  5153.6     .16       0  5207.1     .07       0
Bank Sta=5004.6,5009.3
XS Rating Curve= 0 ,0
Exp/Cntr=0.3,0.1

Type RM Length L Ch R = 1 ,9902    ,148,148,148
BEGIN DESCRIPTION:
Elm 74 9901.83
END DESCRIPTION:
XS GIS Cut Line= 3
       1530430.4      6764623.44      1530653.96       6764523.6
      1530875.29      6764465.01
#Sta/Elev= 30
  4754.4 2122.81  4760.2 2120.08  4777.9  2119.4  4783.4  2116.3  4801.2 2114.98
  4806.6  2111.4  4824.4 2109.05  4836.1 2105.26  4853.1  2103.6  4876.3 2097.14
  4890.9 2091.23    4905 2087.95  4922.7 2087.84  4928.2 2090.44  4951.4 2088.27
  4956.9 2090.12  4967.5  2085.6  4974.6 2078.89  4980.1 2080.37  4997.1 2074.71
  5008.3 2074.44  5008.7 2073.94    5013 2074.44  5031.4 2077.36  5043.8 2077.81
  5062.4 2082.16    5119 2083.75  5154.1 2093.45  5176.2 2097.66  5228.2 2098.67
#Mann= 3 ,-1 , 0
  4754.4     .07       0  5008.3     .07       0    5013     .07       0
Bank Sta=5008.3,5013
XS Rating Curve= 0 ,0
Exp/Cntr=0.3,0.1

Type RM Length L Ch R = 1 ,9754    ,161,161,161
BEGIN DESCRIPTION:
Elm 74 9754.47
END DESCRIPTION:
XS GIS Cut Line= 3
      1530523.75      6764768.82      1530677.84      6764664.65
      1530885.38      6764472.25
#Sta/Elev= 30
  4810.9 2139.58  4819.9 2138.55  4825.9 2139.85  4848.6 2140.97  4855.8 2136.14
  4861.9 2126.59  4870.8 2118.27  4884.8 2106.93  4891.8 2103.75  4897.8 2096.59
  4933.8 2077.05  4942.7 2074.09  4954.9 2072.67  4955.3 2072.17  4959.6 2072.67
  4978.7    2075  4996.9 2075.47  5056.3 2074.78  5070.4 2076.31  5077.3 2078.74
  5084.6 2078.25    5113  2080.5  5119.8 2079.73  5127.1 2081.74    5134 2081.84
  5155.5 2085.55  5197.6  2094.7  5211.6 2095.79    5219  2094.8  5279.9    2099
#Mann= 4 ,-1 , 0
  4810.9    .035       0  4954.9     .07       0  4959.6    .035       0
  4996.9     .07       0
Bank Sta=4954.9,4959.6
XS Rating Curve= 0 ,0
Exp/Cntr=0.3,0.1

Type RM Length L Ch R = 1 ,9593    ,156,156,156
BEGIN DESCRIPTION:
Elm 74 9593.03
END DESCRIPTION:
XS GIS Cut Line= 3
      1530630.12       6764812.2       1530818.9      6764642.95
      1530907.89      6764454.11
#Sta/Elev= 30
  4741.5  2135.3    4755 2133.92  4761.7  2127.6  4769.2 2126.09    4776 2118.91
  4783.4 2119.28  4790.2  2112.8  4797.6 2113.39  4804.4 2107.24  4811.9 2106.32
  4818.6 2100.43  4826.1  2099.4  4832.8 2091.67  4837.9  2091.5  4840.3 2091.42
    4847 2082.72  4854.5 2087.27  4861.2 2080.38  4868.7 2082.09  4875.4 2078.18
  4882.4 2080.82  5007.8 2068.98  5008.3 2068.48  5015.3 2068.98  5033.7 2071.42
  5047.4 2083.72  5064.7 2088.15    5093 2089.39  5122.1  2095.8  5203.8 2099.61
#Mann= 4 ,-1 , 0
  4741.5    .035       0  4837.9     .07       0  5007.8     .07       0
  5015.3     .07       0
Bank Sta=5007.8,5015.3
XS Rating Curve= 0 ,0
Exp/Cntr=0.3,0.1

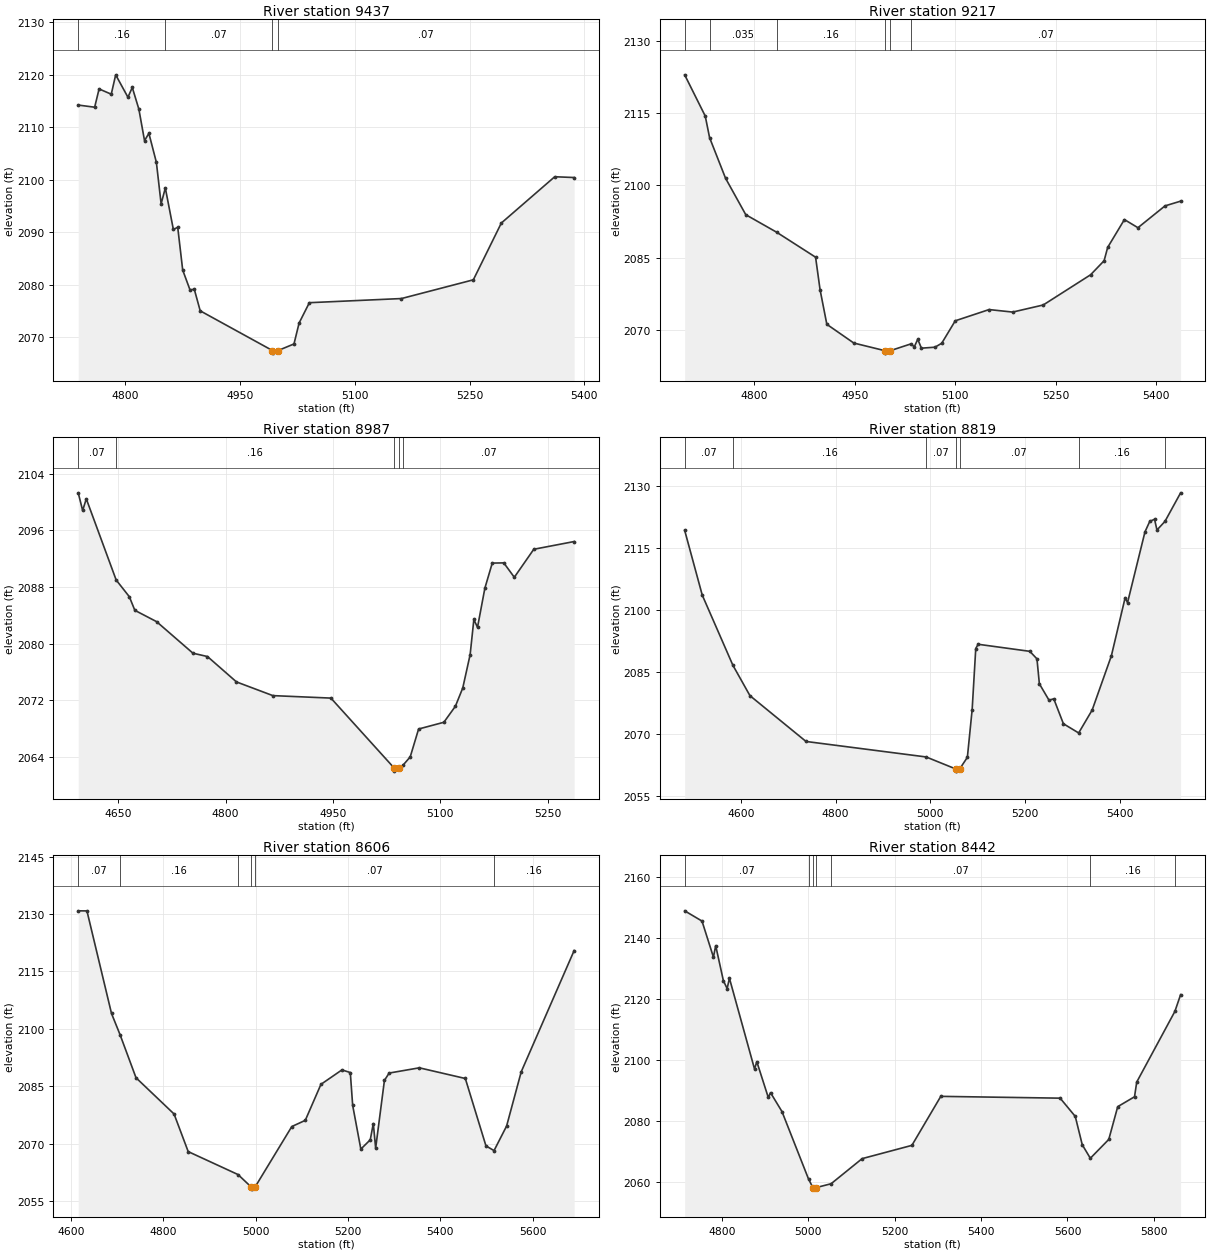
Type RM Length L Ch R = 1 ,9437    ,220,220,220
BEGIN DESCRIPTION:
Elm 74 9436.6
END DESCRIPTION:
XS GIS Cut Line= 3
      1530625.73      6764886.02      1530851.45      6764760.14
      1531239.86      6764794.86
#Sta/Elev= 30
  4738.2  2114.2  4759.7 2113.79  4765.5 2117.27  4781.4 2116.27  4787.2 2119.96
  4803.2 2115.69  4808.9 2117.55  4817.5 2113.42  4824.9 2107.42  4830.6 2108.81
  4840.4 2103.28  4846.6 2095.38  4852.1  2098.4  4862.6 2090.49  4868.3 2090.91
  4874.8 2082.76  4884.3    2079    4890 2079.08  4897.7 2074.99  4992.1 2067.43
  4992.6 2066.93  4999.6 2067.43  5020.3 2068.68    5027 2072.67  5040.4 2076.54
  5160.8 2077.33  5254.8  2080.9  5291.4 2091.72  5361.2 2100.54  5386.6 2100.39
#Mann= 4 ,-1 , 0
  4738.2     .16       0  4852.1     .07       0  4992.1     .07       0
  4999.6     .07       0
Bank Sta=4992.1,4999.6
XS Rating Curve= 0 ,0
Exp/Cntr=0.3,0.1

Type RM Length L Ch R = 1 ,9217    ,230,230,230
BEGIN DESCRIPTION:
Elm 74 9217.31
END DESCRIPTION:
XS GIS Cut Line= 3
      1530584.53      6765007.54      1530890.51      6764968.47
      1531318.05      6764907.71
#Sta/Elev= 30
  4696.2 2122.92  4726.9 2114.36  4733.4 2109.87  4757.2 2101.46  4787.4 2093.89
  4833.5 2090.25  4891.6 2085.07  4898.3 2078.32  4908.4 2071.14  4948.7 2067.25
  4995.3 2065.66  4995.8 2065.16  5002.9 2065.66  5033.8 2067.07    5039 2066.48
  5044.1 2068.04  5049.6 2066.19  5069.8 2066.39  5079.9 2067.21  5100.1 2071.87
  5150.6  2074.2  5185.8 2073.68  5231.4 2075.15  5302.1 2081.42  5322.3 2084.34
  5327.6  2087.1  5352.6 2092.88  5372.8 2091.19  5413.2 2095.72  5436.5  2096.7
#Mann= 6 ,-1 , 0
  4696.2     .07       0  4733.4    .035       0  4833.5     .16       0
  4995.3     .07       0  5002.9     .16       0  5033.8     .07       0
Bank Sta=4995.3,5002.9
XS Rating Curve= 0 ,0
Exp/Cntr=0.3,0.1

Type RM Length L Ch R = 1 ,8987    ,168,168,168
BEGIN DESCRIPTION:
Elm 74 8987.23
END DESCRIPTION:
XS GIS Cut Line= 3
      1530667.02      6765031.41      1531085.82      6765103.02
      1531346.25      6765040.09
#Sta/Elev= 30
    4594 2101.28  4600.2 2098.79  4605.3 2100.43    4647 2088.99  4665.4 2086.63
  4673.1 2084.71  4703.5 2083.11  4754.3 2078.66  4774.6 2078.19  4815.1 2074.61
  4865.9 2072.68    4947 2072.33  5034.8 2062.53  5035.3 2062.03  5042.4 2062.53
  5047.5 2062.84  5057.8 2064.04  5069.5 2067.97  5104.8 2068.92  5120.9 2071.18
  5131.2 2073.76  5141.5 2078.46  5146.7 2083.42  5151.8 2082.31  5162.1 2087.84
  5172.4 2091.37  5188.5  2091.4  5203.2 2089.37  5230.4 2093.32  5286.8 2094.41
#Mann= 5 ,-1 , 0
    4594     .07       0    4647     .16       0  5034.8     .07       0
  5042.4     .16       0  5047.5     .07       0
Bank Sta=5034.8,5042.4
XS Rating Curve= 0 ,0
Exp/Cntr=0.3,0.1

Type RM Length L Ch R = 1 ,8819    ,213,213,213
BEGIN DESCRIPTION:
Elm 74 8819.35
END DESCRIPTION:
XS GIS Cut Line= 3
      1530619.25      6765085.66      1531150.93      6765233.23
      1531639.24       6765155.1
#Sta/Elev= 30
  4481.6 2119.35  4518.7 2103.67  4583.3  2086.7  4619.3 2079.34  4737.6 2068.25
    4991  2064.5    5054 2061.57  5054.5 2061.07  5061.6 2061.57    5078 2064.41
  5088.1 2075.97  5095.7 2090.75  5100.7 2091.78  5209.7 2090.07  5224.8 2088.25
  5229.9 2082.21  5250.2 2078.25  5260.3 2078.57  5280.6 2072.54  5312.8 2070.31
  5341.3 2075.86  5381.8 2088.98  5410.9 2103.07  5415.9 2101.85  5452.7 2118.99
  5462.8 2121.53  5472.9 2122.04    5478 2119.44  5494.9 2121.53  5527.9 2128.44
#Mann= 7 ,-1 , 0
  4481.6     .07       0  4583.3     .16       0    4991     .07       0
    5054     .07       0  5061.6     .07       0  5312.8     .16       0
  5494.9     .07       0
Bank Sta=5054,5061.6
XS Rating Curve= 0 ,0
Exp/Cntr=0.3,0.1

Type RM Length L Ch R = 1 ,8606    ,164,164,164
BEGIN DESCRIPTION:
Elm 74 8605.82
END DESCRIPTION:
XS GIS Cut Line= 3
        1530565.      6765124.73       1531051.1      6765326.55
      1531587.11       6765213.7
#Sta/Elev= 30
  4615.5 2130.84  4634.4 2130.82  4687.6 2104.01    4706  2098.5  4740.7  2087.2
  4823.1 2077.73  4853.7  2067.9  4961.6  2061.9  4990.7 2058.59  4991.2 2058.09
  4998.3 2058.59  5078.1 2074.45  5107.3 2076.07  5141.2 2085.48  5186.7 2089.26
  5204.8 2088.56  5209.9    2080  5227.6 2068.55    5248 2070.98  5254.6 2075.23
  5259.7 2068.81  5278.7 2086.51  5288.9 2088.43  5354.3  2089.8  5453.9 2087.01
  5498.6 2069.39  5516.1 2068.16  5543.3 2074.58    5575 2088.77  5689.6 2120.46
#Mann= 6 ,-1 , 0
  4615.5     .07       0    4706     .16       0  4961.6     .07       0
  4990.7     .07       0  4998.3     .07       0  5516.1     .16       0
Bank Sta=4990.7,4998.3
XS Rating Curve= 0 ,0
Exp/Cntr=0.3,0.1

Type RM Length L Ch R = 1 ,8442    ,154,154,154
BEGIN DESCRIPTION:
Elm 74 8441.9
END DESCRIPTION:
XS GIS Cut Line= 4
      1530499.91      6765231.07      1530775.49      6765322.21
      1531038.08      6765356.93      1531617.53      6765231.06
#Sta/Elev= 30
  4713.8 2149.03  4753.9 2145.67  4780.4 2133.83  4785.6 2137.61  4803.4 2126.12
  4812.1 2123.54  4817.4 2126.92  4875.5 2097.16  4880.8 2099.56  4907.3 2087.84
  4912.5  2089.4    4939 2083.22  5000.5 2061.09  5010.6 2058.27  5011.1 2057.77
  5018.2 2058.27  5052.8 2059.54  5124.6 2067.77  5239.8 2072.12  5306.7 2088.19
    5583  2087.6    5618 2081.62  5634.2 2072.32  5652.9 2067.89  5695.6 2074.07
  5716.3 2084.81  5755.2 2088.06  5760.3 2092.88  5848.6 2116.04  5861.9 2121.55
#Mann= 7 ,-1 , 0
  4713.8     .07       0  5000.5     .16       0  5010.6     .07       0
  5018.2     .16       0  5052.8     .07       0  5652.9     .16       0
  5848.6     .07       0
Bank Sta=5010.6,5018.2
XS Rating Curve= 0 ,0
Exp/Cntr=0.3,0.1

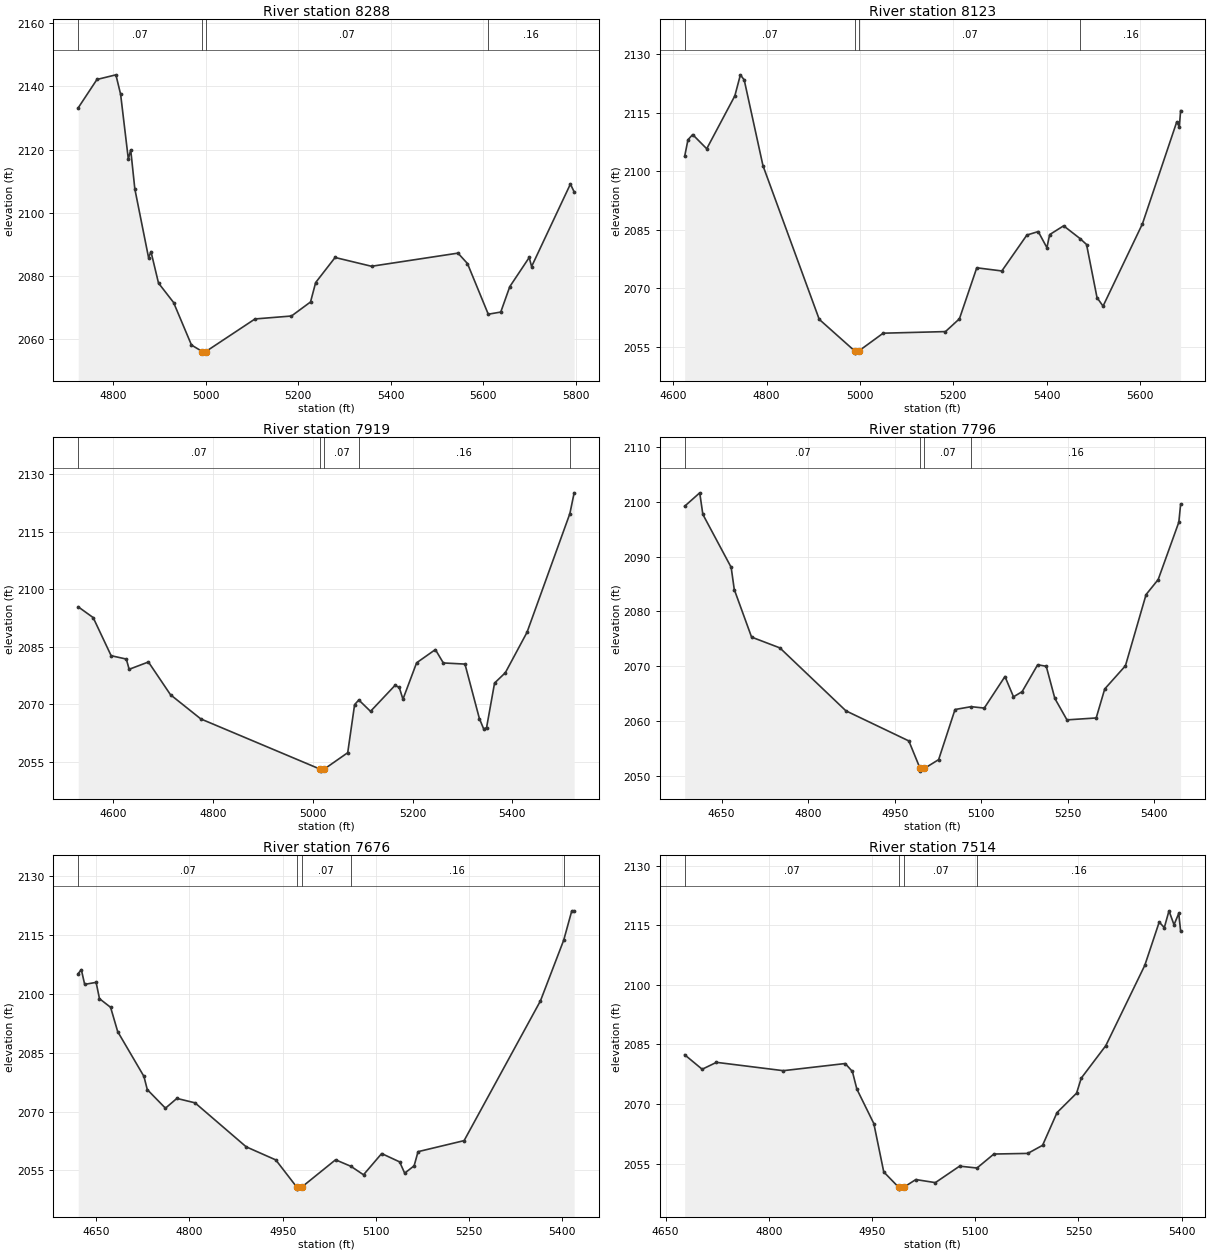
Type RM Length L Ch R = 1 ,8288    ,165,165,165
BEGIN DESCRIPTION:
Elm 74 8287.92
END DESCRIPTION:
XS GIS Cut Line= 3
      1530545.43      6765389.48      1530812.38      6765448.07
      1531589.28      6765261.45
#Sta/Elev= 30
  4724.3 2133.19  4764.8 2142.16  4805.8 2143.63    4816 2137.46  4832.7 2116.93
  4837.8 2119.93  4846.7 2107.56  4876.5 2085.76  4881.6 2087.73  4897.9 2077.77
  4930.5 2071.62  4969.2 2058.17  4992.6 2056.11  4993.1 2055.61  5000.2 2056.11
  5106.6 2066.42  5185.4 2067.35  5226.6 2071.79  5237.7 2077.93  5279.7 2085.86
  5358.5 2083.08  5545.4 2087.24  5565.9 2083.95  5610.9 2067.92  5637.9  2068.6
  5657.4 2076.63  5699.4 2085.86  5704.6 2082.99  5788.5 2109.09  5796.6 2106.61
#Mann= 4 ,-1 , 0
  4724.3     .07       0  4992.6     .07       0  5000.2     .07       0
  5610.9     .16       0
Bank Sta=4992.6,5000.2
XS Rating Curve= 0 ,0
Exp/Cntr=0.3,0.1

Type RM Length L Ch R = 1 ,8123    ,204,204,204
BEGIN DESCRIPTION:
Elm 74 8123.12
END DESCRIPTION:
XS GIS Cut Line= 3
      1530578.01      6765563.09      1530951.27      6765530.54
      1531591.84      6765281.67
#Sta/Elev= 30
  4624.8 2103.81  4631.8 2108.05  4641.9 2109.39    4672 2105.75  4732.2 2119.31
  4744.1  2124.7  4752.3 2123.38  4792.4 2101.43  4912.9 2062.03  4989.4 2053.87
  4989.9 2053.37    4997 2053.87  5049.8 2058.48  5183.2 2058.89  5213.1 2062.17
  5250.2 2075.24  5303.9 2074.43  5357.5 2083.63  5381.8 2084.53  5400.4  2080.4
  5406.3 2083.75  5436.2    2086  5471.6 2082.71  5485.3 2081.21  5507.7  2067.6
  5520.6 2065.41  5604.9  2086.5  5678.5 2112.67  5683.9 2111.34  5686.7 2115.53
#Mann= 4 ,-1 , 0
  4624.8     .07       0  4989.4     .07       0    4997     .07       0
  5471.6     .16       0
Bank Sta=4989.4,4997
XS Rating Curve= 0 ,0
Exp/Cntr=0.3,0.1

Type RM Length L Ch R = 1 ,7919    ,123,123,123
BEGIN DESCRIPTION:
Elm 74 7918.61
END DESCRIPTION:
XS GIS Cut Line= 3
      1530736.43      6765758.41      1531159.61      6765539.22
      1531610.49       6765285.6
#Sta/Elev= 30
  4529.8 2095.42  4559.8 2092.61  4595.8 2082.66  4626.2 2081.78  4631.9 2079.11
  4670.5 2081.02  4714.8 2072.46  4775.5 2066.15  5014.9 2053.02  5015.4 2052.52
  5022.5 2053.02  5069.9 2057.33  5083.7 2069.88  5092.1  2071.1  5115.6 2068.13
  5164.7 2074.91  5173.2 2074.37  5180.6  2071.3    5208 2080.81  5245.6 2084.26
  5261.5 2080.77  5304.9 2080.47  5333.8 2066.24  5342.5 2063.51  5348.2 2063.89
  5364.2 2075.52  5385.8 2078.22  5429.2 2088.76  5515.1 2119.76  5523.7 2125.19
#Mann= 5 ,-1 , 0
  4529.8     .07       0  5014.9     .07       0  5022.5     .07       0
  5092.1     .16       0  5515.1     .07       0
Bank Sta=5014.9,5022.5
XS Rating Curve= 0 ,0
Exp/Cntr=0.3,0.1

Type RM Length L Ch R = 1 ,7796    ,120,120,120
BEGIN DESCRIPTION:
Elm 74 7795.59
END DESCRIPTION:
XS GIS Cut Line= 3
      1530827.55      6765793.14      1531209.52      6765645.56
      1531580.32      6765389.69
#Sta/Elev= 30
  4585.9  2099.2    4612 2101.64  4617.4 2097.71  4666.5 2088.05  4671.9    2084
  4701.9 2075.32    4751 2073.35  4865.5 2061.87  4974.6 2056.38  4994.1 2051.37
  4994.6 2050.87  5001.7 2051.37  5026.3 2052.97  5054.7 2062.11  5082.7 2062.63
  5105.4 2062.37  5141.3 2068.13  5156.1 2064.43    5171 2065.36    5198 2070.27
  5212.9    2070  5227.8 2064.13  5248.8 2060.22  5299.5 2060.57  5314.3 2065.86
  5350.2 2070.09    5386 2083.08    5407 2085.82  5442.8 2096.29  5445.9 2099.55
#Mann= 4 ,-1 , 0
  4585.9     .07       0  4994.1     .07       0  5001.7     .07       0
  5082.7     .16       0
Bank Sta=4994.1,5001.7
XS Rating Curve= 0 ,0
Exp/Cntr=0.3,0.1

Type RM Length L Ch R = 1 ,7676    ,162,162,162
BEGIN DESCRIPTION:
Elm 74 7676.23
END DESCRIPTION:
XS GIS Cut Line= 3
      1530946.96      6765875.58      1531289.82      6765732.36
      1531656.56      6765515.36
#Sta/Elev= 30
  4621.2  2105.1  4626.2  2106.1  4631.6 2102.35    4650 2102.86  4655.4 2098.71
  4673.3 2096.51  4684.7 2090.33  4726.9 2078.94  4732.3 2075.58  4761.5 2070.85
  4779.9 2073.34  4809.1 2072.21  4891.4 2061.02    4939 2057.69  4972.8 2050.76
  4973.3 2050.26  4980.6 2050.76  5035.1 2057.72  5059.8 2056.07  5080.1 2053.91
  5109.3 2059.31  5138.2 2057.19  5146.3 2054.32  5161.5 2056.19  5167.8 2059.79
  5241.9  2062.6  5364.7 2098.16  5402.1  2113.6  5415.1 2121.06  5418.9 2121.06
#Mann= 5 ,-1 , 0
  4621.2     .07       0  4972.8     .07       0  4980.6     .07       0
  5059.8     .16       0  5402.1     .07       0
Bank Sta=4972.8,4980.6
XS Rating Curve= 0 ,0
Exp/Cntr=0.3,0.1

Type RM Length L Ch R = 1 ,7514    ,148,148,148
BEGIN DESCRIPTION:
Elm 74 7513.67
END DESCRIPTION:
XS GIS Cut Line= 3
      1531120.54      6765901.64      1531426.53      6765814.83
      1531720.81      6765540.03
#Sta/Elev= 30
  4677.8 2082.41  4703.2 2078.76    4724  2080.5  4821.1  2078.4  4911.1  2080.2
  4921.5  2078.2    4928 2073.77  4952.7 2065.06  4967.1 2052.89  4988.6 2049.06
  4989.1 2048.56  4996.4 2049.06  5013.7 2050.97  5042.1  2050.2  5077.3 2054.35
  5102.6 2053.88  5127.1  2057.4  5176.4 2057.56  5197.9  2059.6  5218.9 2067.84
  5247.3 2072.73  5254.1 2076.52  5289.8 2084.71  5346.4 2104.92  5367.4 2115.84
  5374.8 2114.43  5381.6 2118.67  5388.9 2115.16  5395.8 2118.02  5398.5 2113.59
#Mann= 4 ,-1 , 0
  4677.8     .07       0  4988.6     .07       0  4996.4     .07       0
  5102.6     .16       0
Bank Sta=4988.6,4996.4
XS Rating Curve= 0 ,0
Exp/Cntr=0.3,0.1

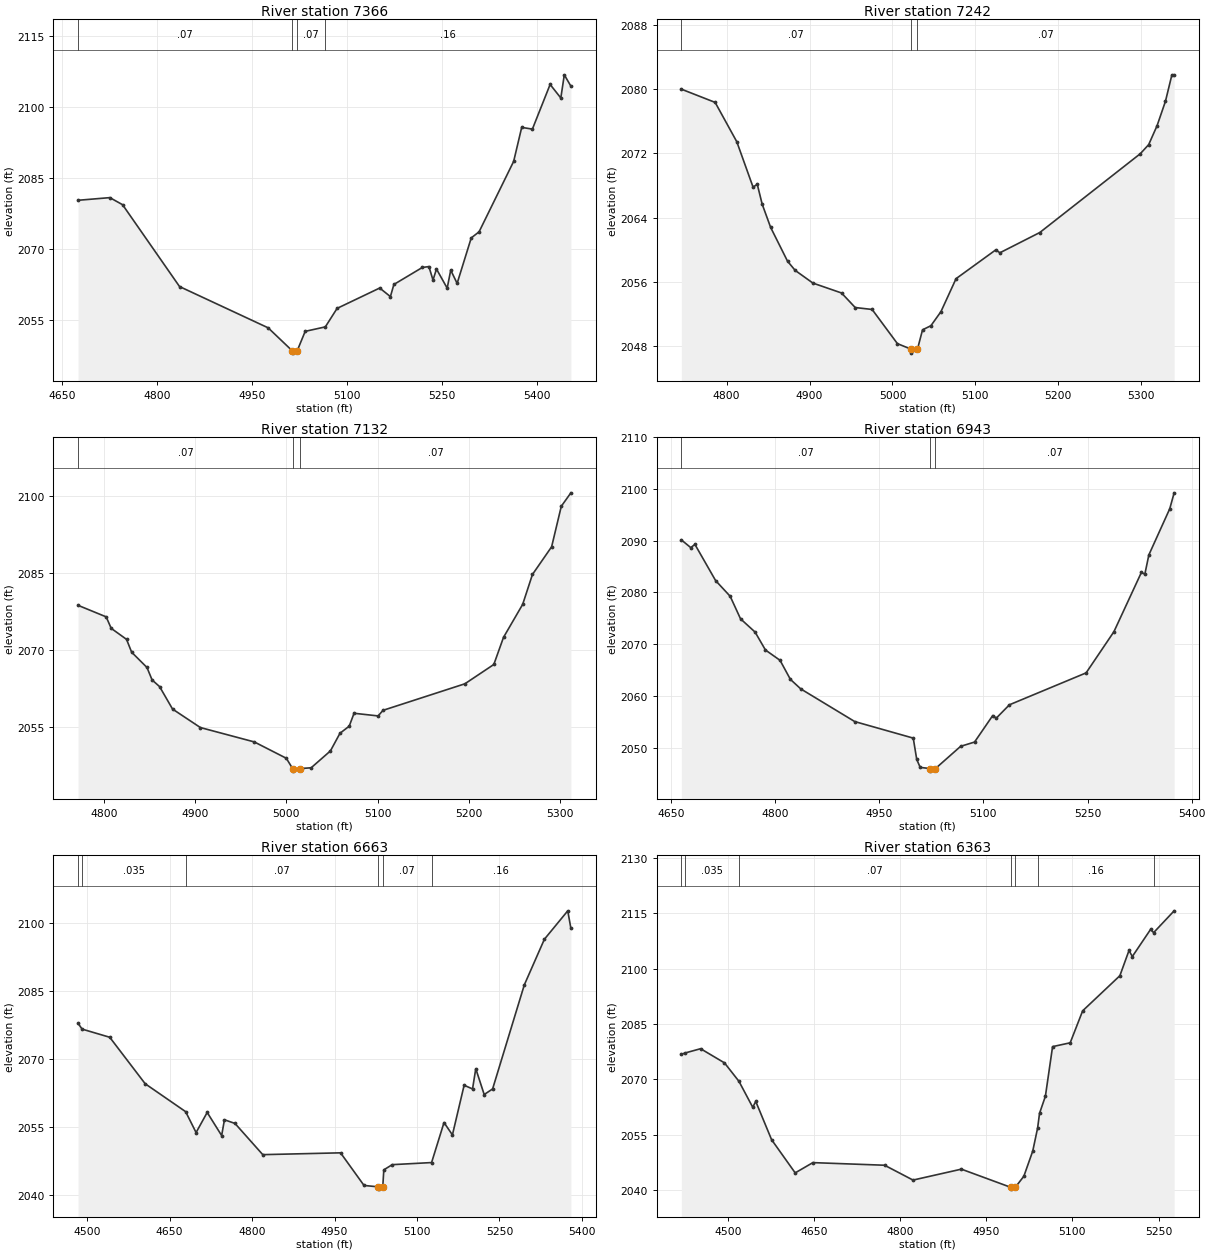
Type RM Length L Ch R = 1 ,7366    ,124,124,124
BEGIN DESCRIPTION:
Elm 74 7365.51
END DESCRIPTION:
XS GIS Cut Line= 3
      1531224.76      6765892.95      1531548.06      6765888.61
      1531956.04       6765686.8
#Sta/Elev= 30
  4674.9 2080.29  4725.1 2080.85  4745.2 2079.36  4835.2 2062.11  4975.2 2053.41
  5013.2 2048.58  5013.7 2048.08  5021.1 2048.58  5033.7 2052.67  5065.5 2053.61
  5084.1 2057.51  5151.4  2061.8  5168.3 2059.99  5173.8 2062.55  5218.7 2066.13
  5229.1 2066.32  5235.6 2063.48  5241.1  2065.8    5258 2061.77  5263.6 2065.56
  5273.7 2062.78    5296 2072.36  5308.4 2073.65    5363 2088.49  5375.7 2095.65
  5392.6 2095.29  5420.6  2104.7  5437.5 2101.85    5443 2106.73  5453.4 2104.34
#Mann= 4 ,-1 , 0
  4674.9     .07       0  5013.2     .07       0  5021.1     .07       0
  5065.5     .16       0
Bank Sta=5013.2,5021.1
XS Rating Curve= 0 ,0
Exp/Cntr=0.3,0.1

Type RM Length L Ch R = 1 ,7242    ,110,110,110
BEGIN DESCRIPTION:
Elm 74 7241.83
END DESCRIPTION:
XS GIS Cut Line= 3
      1531259.44      6765945.04      1531506.83      6765994.95
       1531845.4       6766042.7
#Sta/Elev= 30
  4745.4 2079.97  4786.2 2078.32  4812.3 2073.43  4831.9 2067.79    4837 2068.13
  4842.9 2065.67  4853.1 2062.78  4873.5 2058.57  4882.7 2057.43  4904.1 2055.85
  4938.6 2054.62  4955.1 2052.81  4975.5 2052.57    5006 2048.32  5022.3 2047.64
  5022.8 2047.14  5030.2 2047.64  5036.3 2050.04  5046.4 2050.55  5058.5  2052.3
  5076.7  2056.4  5124.6 2059.98  5129.6 2059.62  5177.7 2062.14  5298.9 2071.94
    5309 2073.07  5319.1 2075.42  5329.2 2078.45    5337 2081.75  5339.7 2081.75
#Mann= 3 ,-1 , 0
  4745.4     .07       0  5022.3     .07       0  5030.2     .07       0
Bank Sta=5022.3,5030.2
XS Rating Curve= 0 ,0
Exp/Cntr=0.3,0.1

Type RM Length L Ch R = 1 ,7132    ,189,189,189
BEGIN DESCRIPTION:
Elm 74 7132.259
END DESCRIPTION:
XS GIS Cut Line= 3
      1531255.03      6765988.01      1531459.19      6766089.74
        1531755.        6766188.
#Sta/Elev= 30
  4771.9 2078.74  4802.7 2076.49  4808.2 2074.25    4825  2072.1  4830.6 2069.59
  4847.4 2066.61    4853 2064.18  4861.2 2062.88  4875.4  2058.5  4905.9 2054.89
  4964.9 2052.09    5000  2048.9  5006.9 2046.89  5007.4 2046.39  5014.8 2046.89
  5027.2 2047.04  5048.3 2050.33  5058.8 2053.78  5068.9 2055.16  5074.2 2057.68
  5100.6 2057.16  5105.9 2058.25  5195.6 2063.43  5227.3  2067.2  5237.9 2072.49
  5258.9 2078.93  5269.6 2084.76  5290.6 2090.16  5301.2 2098.07  5311.7 2100.69
#Mann= 3 ,-1 , 0
  4771.9     .07       0  5006.9     .07       0  5014.8     .07       0
Bank Sta=5006.9,5014.8
XS Rating Curve= 0 ,0
Exp/Cntr=0.3,0.1

Type RM Length L Ch R = 1 ,6943    ,280,280,280
BEGIN DESCRIPTION:
Elm 74 6943.04
END DESCRIPTION:
XS GIS Cut Line= 3
      1531081.46      6766053.53      1531357.09      6766242.35
      1531731.29      6766276.95
#Sta/Elev= 30
  4664.9 2090.17  4678.5 2088.67  4684.5 2089.29  4714.3  2082.3  4735.3 2079.26
  4750.2 2074.91  4771.2 2072.34  4786.1 2068.88  4807.1 2066.89    4822 2063.21
  4836.9 2061.37  4914.7 2055.05    4999 2051.85    5004 2047.74    5009 2046.19
  5023.1 2045.97  5023.6 2045.47    5031 2045.97  5067.2 2050.26  5087.3 2051.09
  5113.5 2056.22  5118.6 2055.71  5137.5 2058.29    5248 2064.46  5288.1 2072.43
  5327.6 2083.87  5332.6 2083.54  5338.4 2087.27  5368.5 2096.19  5374.8 2099.26
#Mann= 3 ,-1 , 0
  4664.9     .07       0  5023.1     .07       0    5031     .07       0
Bank Sta=5023.1,5031
XS Rating Curve= 0 ,0
Exp/Cntr=0.3,0.1

Type RM Length L Ch R = 1 ,6663    ,300,300,300
BEGIN DESCRIPTION:
Elm 74 6662.56
END DESCRIPTION:
XS GIS Cut Line= 3
       1530942.6      6766561.36      1531441.73      6766487.57
      1531773.73      6766279.26
#Sta/Elev= 30
  4483.4 2077.84  4490.8 2076.56    4541 2074.77  4605.5 2064.55  4679.1 2058.41
  4698.1 2053.82  4718.3 2058.24  4744.6 2053.16  4749.7 2056.63  4768.9 2055.82
  4819.4 2048.96  4960.9 2049.36  5003.6 2042.19  5029.6 2041.88  5030.1 2041.38
  5037.7 2041.88  5039.6 2045.62  5054.9 2046.76  5126.5 2047.22  5149.1 2056.02
  5164.4  2053.3  5185.7 2064.22    5201 2063.41  5206.9 2067.86  5222.2 2062.18
  5237.5 2063.41  5295.2 2086.29  5331.7 2096.32  5374.2 2102.57  5379.9 2098.73
#Mann= 6 ,-1 , 0
  4483.4     .07       0  4490.8    .035       0  4679.1     .07       0
  5029.6     .07       0  5037.7     .07       0  5126.5     .16       0
Bank Sta=5029.6,5037.7
XS Rating Curve= 0 ,0
Exp/Cntr=0.3,0.1

Type RM Length L Ch R = 1 ,6363    ,134,134,134
BEGIN DESCRIPTION:
Elm 74 6362.69
END DESCRIPTION:
XS GIS Cut Line= 3
      1531161.75      6766691.57      1531728.18      6766561.36
      1531969.08      6766424.63
#Sta/Elev= 30
    4419 2076.78  4425.1 2077.14  4452.6 2078.32  4494.2 2074.48  4519.4 2069.48
  4543.4 2062.45  4548.6 2064.05  4576.2 2053.68  4617.3 2044.69  4648.1 2047.47
    4773 2046.76  4822.5 2042.74  4906.7  2045.7  4992.5 2040.79    4993 2040.29
  5000.6 2040.79  5015.5 2043.78    5031 2050.61  5039.5 2056.88  5042.8 2060.82
    5053 2065.44  5065.5 2078.88  5096.2 2079.92  5117.9 2088.58  5182.7 2098.09
  5198.6 2104.92  5204.4 2103.29  5236.1 2110.61  5241.5 2109.76  5277.2 2115.66
#Mann= 7 ,-1 , 0
    4419     .07       0  4425.1    .035       0  4519.4     .07       0
  4992.5     .07       0  5000.6     .07       0  5039.5     .16       0
  5241.5     .07       0
Bank Sta=4992.5,5000.6
XS Rating Curve= 0 ,0
Exp/Cntr=0.3,0.1

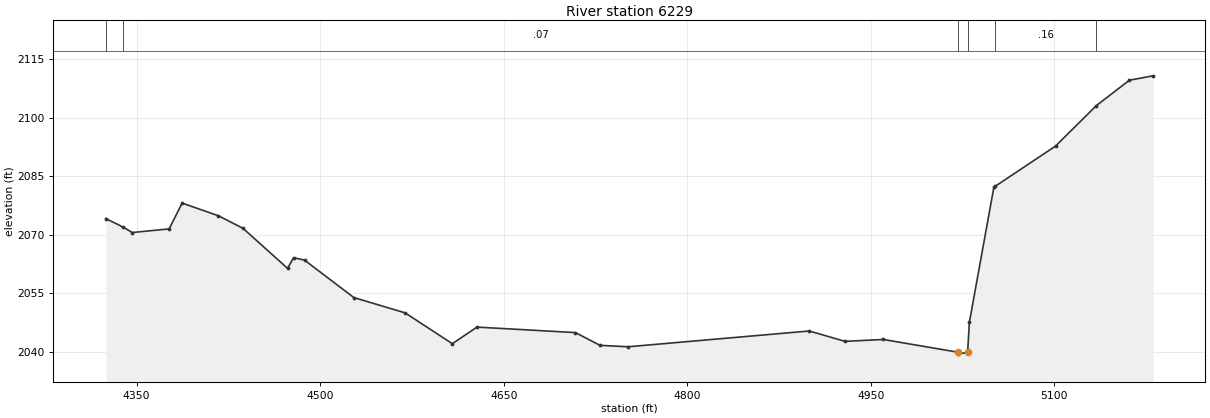
Type RM Length L Ch R = 1 ,6229    ,121,121,121
BEGIN DESCRIPTION:
Elm 74 6228.53
END DESCRIPTION:
XS GIS Cut Line= 3
      1531133.53      6766739.31      1531806.31      6766665.52
      1531984.22        6766646.
#Sta/Elev= 30
  4324.8 2074.14  4339.1 2071.92  4346.4 2070.55  4376.6 2071.48  4387.2  2078.1
  4416.8 2074.85  4436.9 2071.64  4473.3 2061.38  4478.3  2064.1  4487.2 2063.48
  4527.5 2053.88  4569.4 2049.96    4608 2042.05  4628.1 2046.31  4708.6  2044.9
  4728.7 2041.63  4751.7 2041.27  4899.7 2045.31  4928.9 2042.65  4960.1 2043.14
    5021 2039.88  5021.5 2039.38  5029.1 2039.88  5030.5 2047.54  5050.6 2082.27
  5051.8 2082.44  5100.9 2092.71  5134.2 2103.06  5161.3  2109.6  5180.6 2110.72
#Mann= 6 ,-1 , 0
  4324.8    .035       0  4339.1     .07       0    5021     .07       0
  5029.1     .07       0  5051.8     .16       0  5134.2     .07       0
Bank Sta=5021,5029.1
XS Rating Curve= 0 ,0
Exp/Cntr=0.3,0.1