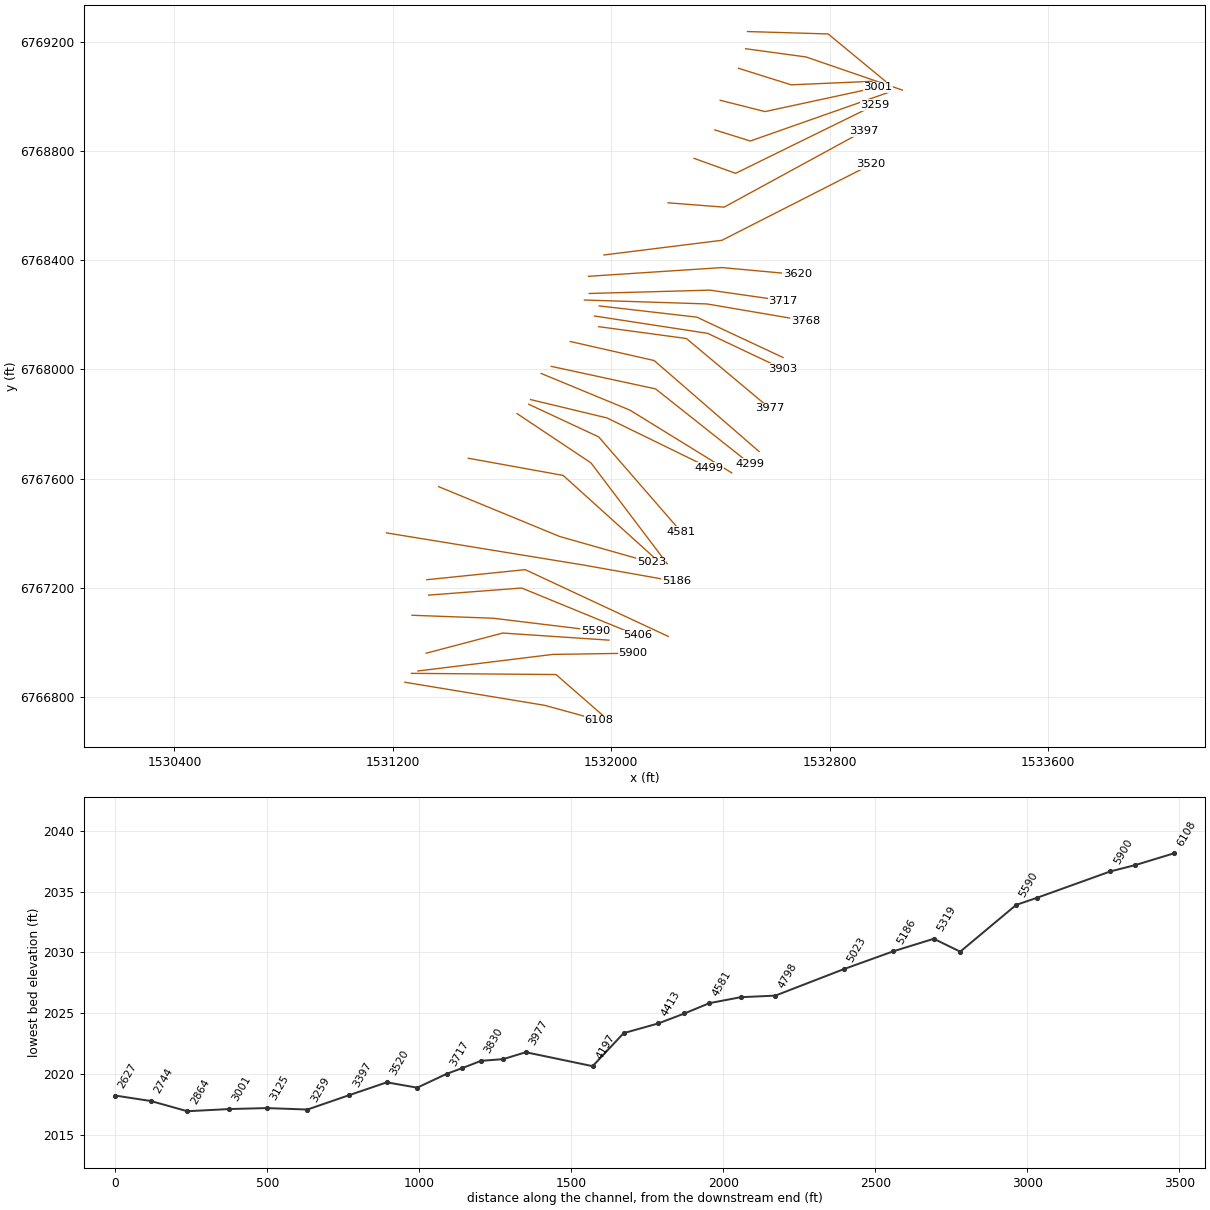
HEC-RAS study Elm 74.prj: Elm 74 Base Level Engineering

--- Elm 74.g01 (geometry) --- (continued)

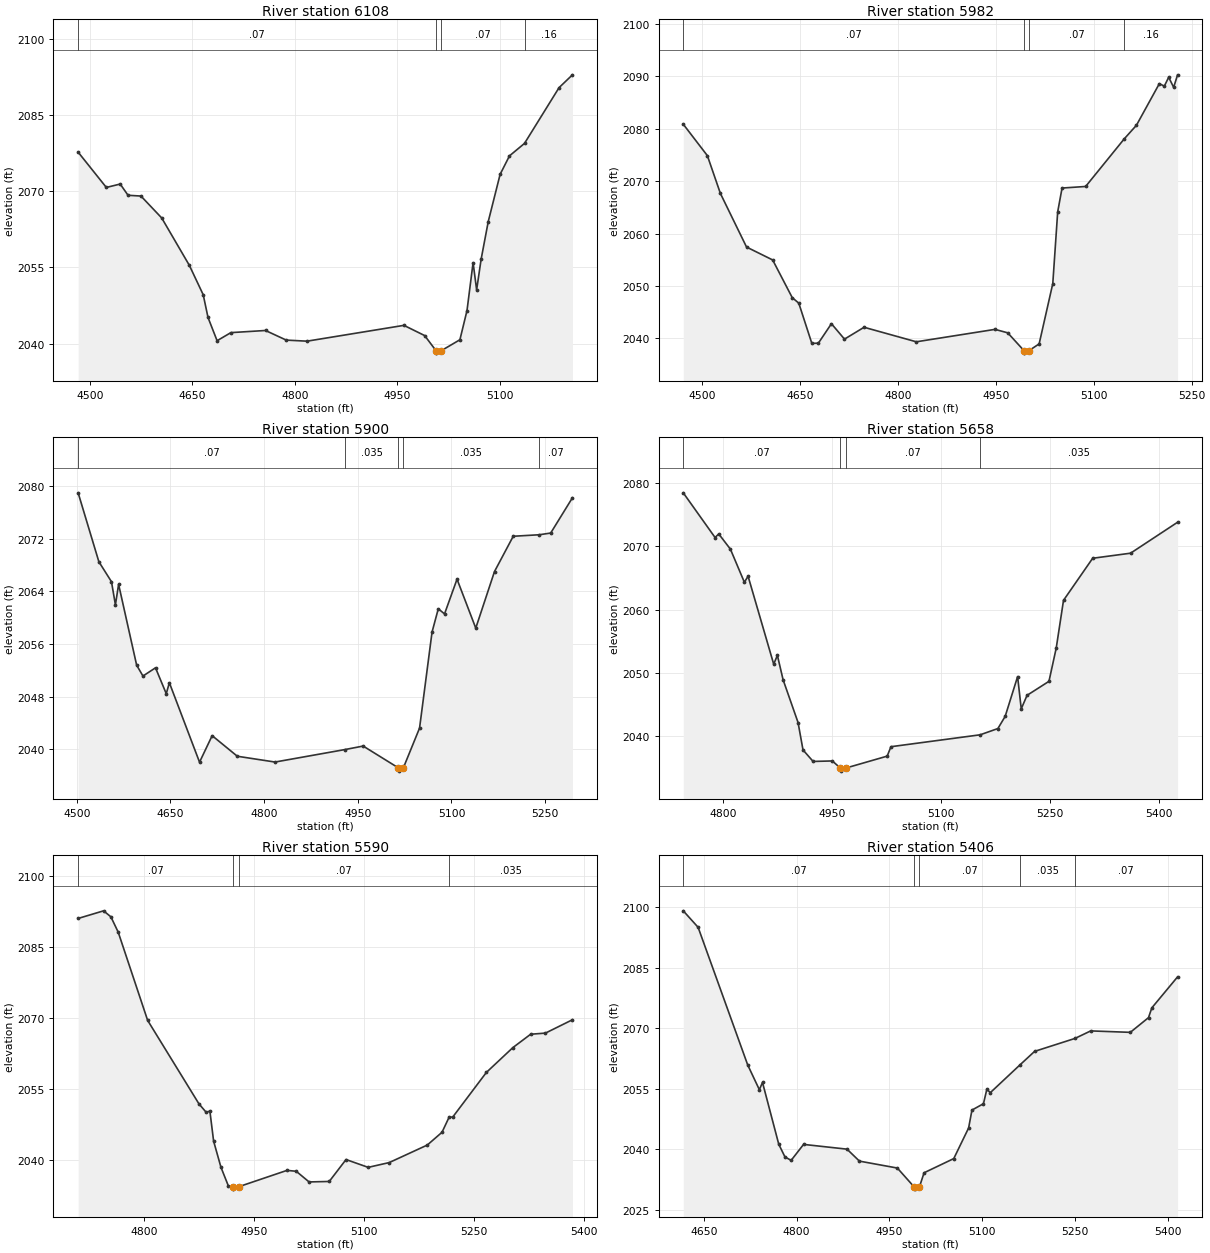
Type RM Length L Ch R = 1 ,6108    ,126,126,126
BEGIN DESCRIPTION:
Elm 74 6108.38
END DESCRIPTION:
XS GIS Cut Line= 3
      1531244.25      6766854.32       1531756.4      6766769.69
      1531953.89      6766715.43
#Sta/Elev= 30
  4482.7 2077.66    4524 2070.72  4544.3 2071.39  4555.8 2069.18  4574.7 2069.03
  4605.1 2064.72  4645.6  2055.4  4665.9 2049.62  4672.9 2045.16  4686.2 2040.59
  4706.4 2042.18  4757.1  2042.6  4787.5 2040.71  4817.9  2040.5  4959.8 2043.61
  4990.2  2041.6  5006.7 2038.65  5007.2 2038.15  5014.8 2038.65  5041.8 2040.78
  5052.2 2046.53  5061.1 2055.94  5066.3 2050.58  5072.9 2056.62  5083.3 2064.01
  5100.7  2073.3  5114.4 2076.93  5136.4 2079.38    5187 2090.34  5206.6 2092.86
#Mann= 4 ,-1 , 0
  4482.7     .07       0  5006.7     .07       0  5014.8     .07       0
  5136.4     .16       0
Bank Sta=5006.7,5014.8
XS Rating Curve= 0 ,0
Exp/Cntr=0.3,0.1

Type RM Length L Ch R = 1 ,5982    ,82,82,82
BEGIN DESCRIPTION:
Elm 74 5981.71
END DESCRIPTION:
XS GIS Cut Line= 3
      1531268.14      6766886.88      1531797.63      6766882.54
      1531968.97      6766732.89
#Sta/Elev= 30
  4471.4 2080.84  4508.3 2074.85  4528.3 2067.63  4568.3 2057.42  4608.3 2054.96
  4638.3 2047.77  4648.3 2046.72  4668.3 2039.05  4678.3 2039.09  4698.3  2042.8
  4718.3 2039.86  4748.3 2042.12  4828.3 2039.35  4948.8 2041.72  4968.3 2041.06
    4993 2037.69  4993.5 2037.19  5001.1 2037.69  5016.4 2038.95  5037.3 2050.45
  5044.8 2064.12  5051.5 2068.67  5087.6 2068.97  5146.8 2078.06  5165.4 2080.64
  5200.5 2088.58  5208.1  2088.1  5214.8  2089.8  5222.4 2087.87  5228.4 2090.26
#Mann= 4 ,-1 , 0
  4471.4     .07       0    4993     .07       0  5001.1     .07       0
  5146.8     .16       0
Bank Sta=4993,5001.1
XS Rating Curve= 0 ,0
Exp/Cntr=0.3,0.1

Type RM Length L Ch R = 1 ,5900    ,242,242,242
BEGIN DESCRIPTION:
Elm 74 5900.27
END DESCRIPTION:
XS GIS Cut Line= 3
      1531292.01      6766895.56      1531786.78      6766956.32
      1532079.76      6766960.66
#Sta/Elev= 30
  4502.2 2078.96  4535.4 2068.49  4555.6 2065.45  4561.9 2061.94    4567 2065.05
  4595.9 2052.77    4606 2051.12  4626.1 2052.37  4643.3 2048.44  4648.3  2050.1
  4696.6 2038.03  4716.8 2042.06  4757.1 2038.93  4817.5 2038.05  4929.6 2039.95
  4958.6 2040.48  5014.9 2037.17  5015.4 2036.67    5023 2037.17  5048.9 2043.21
  5068.9  2057.8  5078.9 2061.34  5088.9 2060.56  5108.9 2065.84  5138.9  2058.4
  5168.9    2067  5198.9 2072.36  5240.7 2072.59  5258.9 2072.85  5293.7 2078.21
#Mann= 5 ,-1 , 0
  4502.2     .07       0  4929.6    .035       0  5014.9    .035       0
    5023    .035       0  5240.7     .07       0
Bank Sta=5014.9,5023
XS Rating Curve= 0 ,0
Exp/Cntr=0.3,0.1

Type RM Length L Ch R = 1 ,5658    ,68,68,68
BEGIN DESCRIPTION:
Elm 74 5657.68
END DESCRIPTION:
XS GIS Cut Line= 3
      1531322.37      6766960.66      1531602.32      6767034.45
      1531991.45       6767008.5
#Sta/Elev= 30
  4745.7 2078.47  4789.4 2071.41  4794.5 2071.97  4810.5 2069.57  4829.7 2064.34
  4834.8 2065.29    4870  2051.4  4875.1 2052.78  4882.9 2048.94  4903.5 2042.17
  4910.3 2037.84  4924.2 2036.02  4950.6  2036.1  4961.5 2034.99    4962 2034.49
  4969.6 2034.99    5026 2036.86  5031.2 2038.35  5153.8 2040.23  5178.2 2041.22
  5188.2 2043.14  5205.3 2049.43  5210.3 2044.33  5218.3 2046.47  5248.4 2048.68
  5258.4 2053.94  5268.4 2061.48  5308.5 2068.13  5360.6 2068.93  5425.2 2073.82
#Mann= 4 ,-1 , 0
  4745.7     .07       0  4961.5     .07       0  4969.6     .07       0
  5153.8    .035       0
Bank Sta=4961.5,4969.6
XS Rating Curve= 0 ,0
Exp/Cntr=0.3,0.1

Type RM Length L Ch R = 1 ,5590    ,184,184,184
BEGIN DESCRIPTION:
Elm 74 5589.62
END DESCRIPTION:
XS GIS Cut Line= 3
       1531270.3      6767099.55      1531567.59       6767088.7
      1531941.56      6767043.31
#Sta/Elev= 30
  4710.3 2091.09    4745  2092.7    4755 2091.43    4765 2088.18  4805.1 2069.56
  4875.1 2051.92    4885 2050.13    4890  2050.4  4895.1 2044.04  4905.1 2038.53
  4915.1 2034.63    4921 2034.41  4921.5 2033.91  4929.2 2034.41  4995.2 2037.87
  5007.8 2037.68  5025.3 2035.43  5052.8 2035.53  5075.7 2040.16  5105.9 2038.51
  5134.6 2039.52  5186.5 2043.22  5206.6 2045.92  5216.1 2049.05  5221.4 2049.17
  5267.1 2058.56  5303.2  2063.8  5327.5 2066.63  5347.7 2066.87  5384.5 2069.69
#Mann= 4 ,-1 , 0
  4710.3     .07       0    4921     .07       0  4929.2     .07       0
  5216.1    .035       0
Bank Sta=4921,4929.2
XS Rating Curve= 0 ,0
Exp/Cntr=0.3,0.1

Type RM Length L Ch R = 1 ,5406    ,87,87,87
BEGIN DESCRIPTION:
Elm 74 5405.55
END DESCRIPTION:
XS GIS Cut Line= 3
      1531331.06      6767173.34      1531671.76      6767199.38
      1532094.94      6767025.77
#Sta/Elev= 30
  4616.7 2099.13  4640.7 2095.04  4720.9 2060.87  4739.7 2054.74  4744.8 2056.54
  4771.1 2041.19  4781.1 2038.05  4791.1  2037.2  4811.2 2041.16  4881.4 2039.98
  4901.5 2037.01  4962.8 2035.29  4990.2 2030.56  4990.7 2030.06  4998.4 2030.56
    5006 2034.12    5054 2037.64    5078 2045.24  5083.4 2049.68    5102 2051.26
  5107.4  2054.8  5113.2 2054.02  5161.4 2060.95  5184.7 2064.25  5249.9 2067.46
  5275.4 2069.33  5339.4 2068.97  5368.8 2072.62  5374.2 2075.05  5415.8 2082.74
#Mann= 5 ,-1 , 0
  4616.7     .07       0  4990.2     .07       0  4998.4     .07       0
  5161.4    .035       0  5249.9     .07       0
Bank Sta=4990.2,4998.4
XS Rating Curve= 0 ,0
Exp/Cntr=0.3,0.1

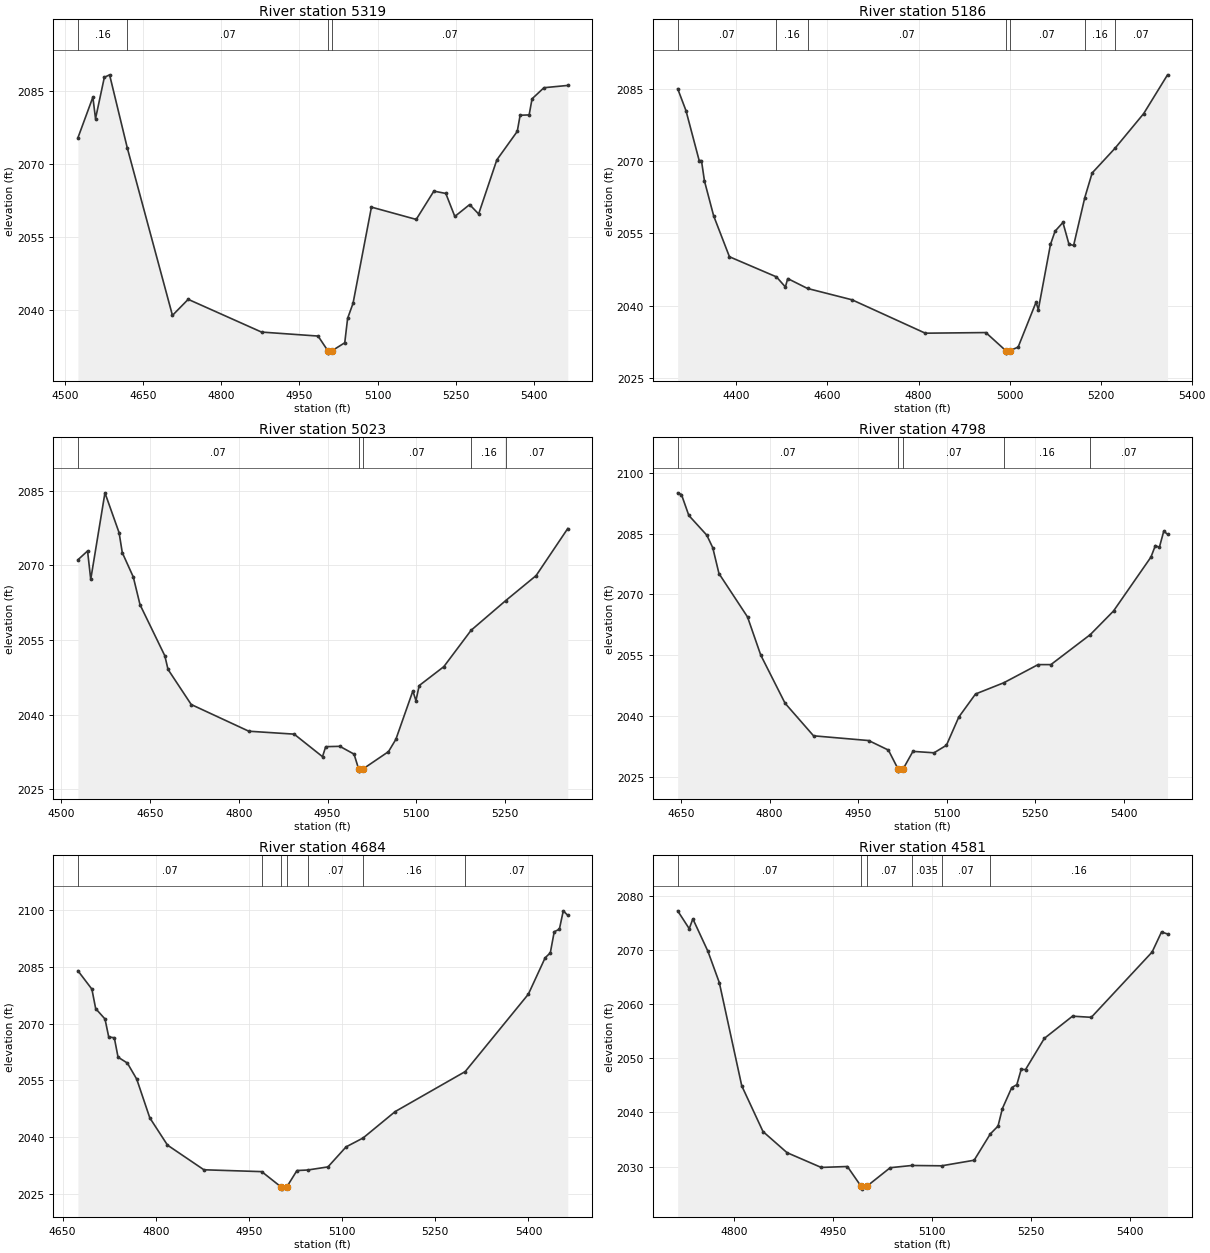
Type RM Length L Ch R = 1 ,5319    ,133,133,133
BEGIN DESCRIPTION:
Elm 74 5318.59
END DESCRIPTION:
XS GIS Cut Line= 3
      1531324.52      6767229.76      1531684.78      6767266.65
      1532208.28      6767022.21
#Sta/Elev= 30
  4524.9 2075.38  4553.6 2083.74  4558.7 2079.33  4575.6 2087.82  4585.7 2088.34
  4619.7 2073.29  4706.3 2038.88  4736.5 2042.18  4877.2 2035.45  4985.7 2034.63
  5004.4 2031.62  5004.9 2031.12  5012.6 2031.62  5036.9 2033.25  5042.4 2038.27
  5052.8 2041.36  5088.1 2061.14    5174 2058.61  5207.9 2064.43  5230.8 2063.95
  5248.1 2059.22  5276.5 2061.66  5293.8 2059.73  5328.7 2070.85  5367.9 2076.71
  5373.4 2080.03  5390.7  2080.1  5396.3 2083.41  5419.1 2085.69  5464.8 2086.16
#Mann= 4 ,-1 , 0
  4524.9     .16       0  4619.7     .07       0  5004.4     .07       0
  5012.6     .07       0
Bank Sta=5004.4,5012.6
XS Rating Curve= 0 ,0
Exp/Cntr=0.3,0.1

Type RM Length L Ch R = 1 ,5186    ,163,163,163
BEGIN DESCRIPTION:
Elm 74 5185.51
END DESCRIPTION:
XS GIS Cut Line= 3
        1531177.      6767401.19      1531895.28      6767284.01
      1532238.17      6767223.25
#Sta/Elev= 30
    4271 2085.13  4289.2 2080.57  4318.2 2070.18  4323.3 2070.14  4329.8 2065.93
    4350 2058.67  4384.7 2050.15    4488 2045.96  4507.6 2043.86  4512.7 2045.61
  4556.2 2043.55    4654 2041.19  4814.9 2034.24  4947.9 2034.37  4991.9 2030.59
  4992.4 2030.09  5000.2 2030.59  5018.8 2031.34  5058.1 2040.67  5063.2 2039.17
  5089.9 2052.73    5100 2055.48  5117.2 2057.29  5130.5 2052.76  5140.7 2052.51
  5165.3 2062.48  5181.4 2067.59  5231.4 2072.71  5294.6 2079.95    5347 2088.02
#Mann= 7 ,-1 , 0
    4271     .07       0    4488     .16       0  4556.2     .07       0
  4991.9     .07       0  5000.2     .07       0  5165.3     .16       0
  5231.4     .07       0
Bank Sta=4991.9,5000.2
XS Rating Curve= 0 ,0
Exp/Cntr=0.3,0.1

Type RM Length L Ch R = 1 ,5023    ,225,225,225
BEGIN DESCRIPTION:
Elm 74 5023.07
END DESCRIPTION:
XS GIS Cut Line= 3
      1531367.95      6767570.47      1531810.65      6767388.18
      1532146.51      6767292.84
#Sta/Elev= 30
    4528 2071.13  4544.3  2072.9  4549.7  2067.2  4573.7  2084.6  4597.6 2076.58
    4603 2072.57  4621.6 2067.67    4633 2062.09  4674.9 2051.82  4680.3 2049.08
  4719.5 2042.02  4816.8 2036.65  4893.5 2036.06  4941.4 2031.53  4946.8 2033.54
  4970.7 2033.61  4994.7 2032.04  5002.3 2029.12  5002.8 2028.62  5010.6 2029.12
  5052.9 2032.54  5065.4 2035.02  5094.1 2044.74  5099.3  2042.8  5104.8 2045.83
  5146.4 2049.63  5192.6 2056.96  5251.1 2062.93  5302.4 2067.95  5355.9 2077.42
#Mann= 5 ,-1 , 0
    4528     .07       0  5002.3     .07       0  5010.6     .07       0
  5192.6     .16       0  5251.1     .07       0
Bank Sta=5002.3,5010.6
XS Rating Curve= 0 ,0
Exp/Cntr=0.3,0.1

Type RM Length L Ch R = 1 ,4798    ,114,114,114
BEGIN DESCRIPTION:
Elm 74 4797.82
END DESCRIPTION:
XS GIS Cut Line= 3
      1531476.43      6767674.64      1531823.67       6767611.7
      1532178.17      6767291.79
#Sta/Elev= 30
  4644.1 2095.07  4650.5 2094.65    4663 2089.49  4693.5 2084.62  4703.6 2081.52
  4714.1 2075.16  4762.5 2064.46  4784.9 2055.06  4826.1 2043.19  4874.4 2035.15
  4967.9 2033.98  5001.3 2031.63  5017.8 2026.94  5018.3 2026.44  5026.1 2026.94
  5042.9 2031.31  5078.7 2030.96  5099.7 2032.82  5120.6 2039.76    5149 2045.46
  5196.9 2048.23  5255.1 2052.71  5276.8 2052.71  5343.6 2060.11  5382.9 2065.92
  5446.4 2079.23  5453.9 2082.08  5460.6  2081.6  5468.1 2085.61  5474.5 2084.85
#Mann= 5 ,-1 , 0
  4644.1     .07       0  5017.8     .07       0  5026.1     .07       0
  5196.9     .16       0  5343.6     .07       0
Bank Sta=5017.8,5026.1
XS Rating Curve= 0 ,0
Exp/Cntr=0.3,0.1

Type RM Length L Ch R = 1 ,4684    ,103,103,103
BEGIN DESCRIPTION:
Elm 74 4683.759
END DESCRIPTION:
XS GIS Cut Line= 3
      1531654.99      6767838.01      1531925.56       6767657.6
      1532204.97      6767288.04
#Sta/Elev= 30
  4674.8 2083.98  4697.3 2079.12  4703.4 2073.98  4718.4 2071.24  4724.4 2066.49
  4733.4 2066.28  4739.4 2061.16  4754.4  2059.6  4769.5 2055.35  4790.5 2045.14
    4819 2037.93  4877.6 2031.42  4970.7 2030.93  5002.4 2026.81  5002.9 2026.31
  5010.7 2026.81  5027.4 2031.22  5044.8 2031.36  5077.3 2032.18  5106.5 2037.47
  5133.8 2039.81  5185.5 2046.79  5298.2 2057.35  5399.9  2077.8  5426.9  2087.4
  5435.2  2088.7  5441.5 2094.27  5449.8 2094.95  5456.1  2099.8  5463.3 2098.61
#Mann= 7 ,-1 , 0
  4674.8     .07       0  4970.7    .035       0  5002.4    .035       0
  5010.7    .035       0  5044.8     .07       0  5133.8     .16       0
  5298.2     .07       0
Bank Sta=5002.4,5010.7
XS Rating Curve= 0 ,0
Exp/Cntr=0.3,0.1

Type RM Length L Ch R = 1 ,4581    ,82,82,82
BEGIN DESCRIPTION:
Elm 74 4581.29
END DESCRIPTION:
XS GIS Cut Line= 3
      1531697.83      6767872.11      1531953.88      6767752.76
       1532255.5      6767405.57
#Sta/Elev= 30
  4714.2 2077.25  4731.7 2073.95  4737.2 2075.77  4760.1 2069.75  4777.3 2063.98
  4811.3 2044.91  4843.5 2036.46  4879.9 2032.56  4931.7 2029.83  4971.4    2030
  4992.3 2026.32  4992.8 2025.82  5000.6 2026.32  5036.3 2029.78  5069.1 2030.19
  5114.2 2030.13  5163.5 2031.16    5188 2036.02  5199.7 2037.47  5206.3 2040.71
  5220.5 2044.59  5228.2 2045.12  5234.8 2047.94  5241.4 2047.92  5269.9 2053.68
  5312.6 2057.78  5341.1 2057.57  5433.2 2069.63  5447.5 2073.35  5456.6 2072.97
#Mann= 6 ,-1 , 0
  4714.2     .07       0  4992.3     .07       0  5000.6     .07       0
  5069.1    .035       0  5114.2     .07       0    5188     .16       0
Bank Sta=4992.3,5000.6
XS Rating Curve= 0 ,0
Exp/Cntr=0.3,0.1

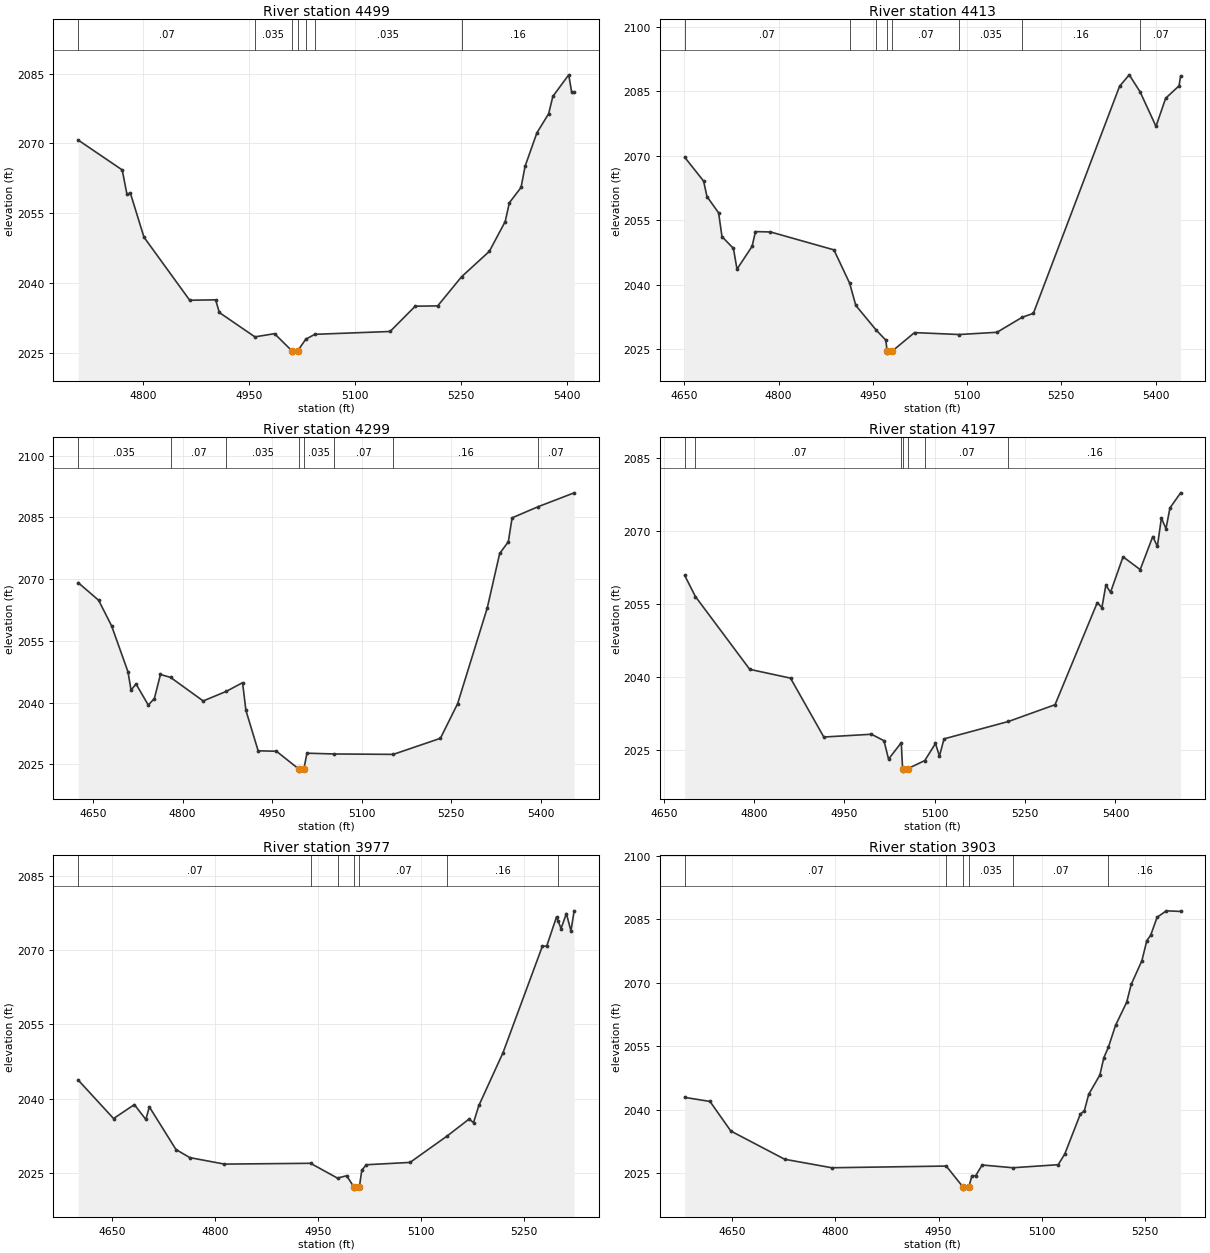
Type RM Length L Ch R = 1 ,4499    ,86,86,86
BEGIN DESCRIPTION:
Elm 74 4499.32
END DESCRIPTION:
XS GIS Cut Line= 3
      1531704.35      6767889.47      1531984.26      6767822.21
      1532357.54       6767639.9
#Sta/Elev= 30
  4707.5 2070.73  4769.9 2064.32  4776.5 2059.18  4781.6 2059.28  4800.7 2049.89
  4865.6 2036.33  4902.4 2036.42  4907.6  2033.7  4958.1 2028.46  4985.9 2029.15
  5010.5 2025.47    5011 2024.97  5018.8 2025.47  5030.2 2027.96  5043.1 2029.01
  5149.8 2029.62  5185.4 2035.05  5217.3 2035.12  5251.1 2041.37  5290.5 2046.83
    5313 2053.23  5318.9 2057.27  5335.5 2060.56  5341.2 2065.11    5358  2072.3
  5374.6 2076.38  5380.6 2080.12  5403.1 2084.75  5407.3 2080.99  5410.8 2080.99
#Mann= 7 ,-1 , 0
  4707.5     .07       0  4958.1    .035       0  5010.5    .035       0
  5018.8    .035       0  5030.2     .07       0  5043.1    .035       0
  5251.1     .16       0
Bank Sta=5010.5,5018.8
XS Rating Curve= 0 ,0
Exp/Cntr=0.3,0.1

Type RM Length L Ch R = 1 ,4413    ,114,114,114
BEGIN DESCRIPTION:
Elm 74 4412.66
END DESCRIPTION:
XS GIS Cut Line= 3
      1531743.33      6767984.99       1532068.9      6767850.42
      1532441.11      6767621.03
#Sta/Elev= 30
  4650.4 2069.65  4680.5 2064.11  4685.9 2060.51  4704.4 2056.73  4709.8  2051.2
    4728 2048.47  4733.7 2043.65  4757.7 2048.95  4763.1 2052.37    4787 2052.29
    4888 2048.13    4913 2040.39  4922.8 2035.23  4955.4 2029.48  4970.6 2027.16
  4972.6 2024.65  4973.1 2024.15    4981 2024.65  5016.3 2028.92  5087.4 2028.47
  5147.6 2028.99  5187.7 2032.48  5205.5 2033.39  5342.7 2086.12  5358.1 2088.78
  5375.4 2084.82  5400.7 2076.81  5416.1 2083.35  5437.4 2086.22  5439.9 2088.52
#Mann= 8 ,-1 , 0
  4650.4     .07       0    4913    .035       0  4955.4     .07       0
  4972.6     .07       0    4981     .07       0  5087.4    .035       0
  5187.7     .16       0  5375.4     .07       0
Bank Sta=4972.6,4981
XS Rating Curve= 0 ,0
Exp/Cntr=0.3,0.1

Type RM Length L Ch R = 1 ,4299    ,102,102,102
BEGIN DESCRIPTION:
Elm 74 4298.86
END DESCRIPTION:
XS GIS Cut Line= 3
      1531780.29        6768011.      1532162.21      6767928.54
      1532507.28       6767655.1
#Sta/Elev= 30
  4625.1 2069.14  4659.3 2064.87  4681.1 2058.63  4708.5 2047.48  4713.6 2043.04
    4722 2044.52  4742.5 2039.41  4752.7 2040.98  4762.9 2046.83  4779.8 2046.13
  4834.5  2040.4  4873.1 2042.72  4900.5 2044.84  4906.1 2038.11  4926.6 2028.29
  4957.3 2028.18  4994.8 2023.85  4995.3 2023.35  5003.2 2023.85  5008.4 2027.71
  5053.3 2027.52    5153 2027.42    5232 2031.32  5260.8 2039.73  5310.5    2063
  5331.3 2076.23  5345.8 2079.08  5352.1 2084.89  5395.9 2087.61  5456.1 2090.97
#Mann= 8 ,-1 , 0
  4625.1    .035       0  4779.8     .07       0  4873.1    .035       0
  4994.8    .035       0  5003.2    .035       0  5053.3     .07       0
    5153     .16       0  5395.9     .07       0
Bank Sta=4994.8,5003.2
XS Rating Curve= 0 ,0
Exp/Cntr=0.3,0.1

Type RM Length L Ch R = 1 ,4197    ,220,220,220
BEGIN DESCRIPTION:
Elm 74 4196.707
END DESCRIPTION:
XS GIS Cut Line= 3
      1531849.71      6768102.16      1532157.08      6768032.34
        1532541.      6767699.36
#Sta/Elev= 30
  4684.8 2060.92  4702.6 2056.57  4792.8 2041.58  4860.5 2039.77  4915.8 2027.65
  4994.9 2028.22  5015.7 2026.89  5023.3 2023.11  5044.4 2026.48  5046.6 2021.13
  5047.1 2020.63    5055 2021.13  5083.4  2022.8  5101.2 2026.32  5107.8 2023.73
  5115.4 2027.27  5222.4 2030.85  5299.7  2034.3  5369.9 2055.33  5377.5 2054.27
  5384.1 2058.91  5391.8 2057.43  5412.6 2064.74  5441.1 2062.11    5462 2068.92
  5469.6  2066.9  5476.3 2072.72  5483.9 2070.53  5490.5  2074.8  5508.2 2077.91
#Mann= 7 ,-1 , 0
  4684.8    .035       0  4702.6     .07       0  5044.4    .035       0
  5046.6     .07       0    5055    .035       0  5083.4     .07       0
  5222.4     .16       0
Bank Sta=5046.6,5055
XS Rating Curve= 0 ,0
Exp/Cntr=0.3,0.1

Type RM Length L Ch R = 1 ,3977    ,74,74,74
BEGIN DESCRIPTION:
Elm 74 4202
END DESCRIPTION:
XS GIS Cut Line= 3
      1531953.92       6768156.4      1532275.06      6768113.01
      1532580.54      6767857.36
#Sta/Elev= 30
  4601.2 2043.78  4652.7 2036.02    4683 2038.83  4699.7 2035.83  4704.8 2038.37
  4743.6 2029.77  4763.7 2028.14  4814.2 2026.83  4939.6 2026.99  4978.9    2024
  4992.2 2024.49  5002.4 2022.28  5002.9 2021.78  5010.8 2022.28  5014.3  2025.6
  5020.9  2026.7  5084.6 2027.17    5139 2032.54  5170.5 2035.91    5177  2035.2
  5184.8 2038.65  5219.9 2049.28  5277.2 2070.74  5283.7 2070.84    5298 2076.73
  5300.4 2075.85  5304.5 2074.34  5312.3 2077.38  5318.9 2073.86  5323.6 2077.92
#Mann= 7 ,-1 , 0
  4601.2     .07       0  4939.6    .035       0  4978.9     .07       0
  5002.4     .07       0  5010.8     .07       0    5139     .16       0
  5300.4     .07       0
Bank Sta=5002.4,5010.8
XS Rating Curve= 0 ,0
Exp/Cntr=0.3,0.1

Type RM Length L Ch R = 1 ,3903    ,73,73,73
BEGIN DESCRIPTION:
Elm 74 4201
END DESCRIPTION:
XS GIS Cut Line= 3
      1531938.67      6768195.47      1532353.02      6768131.87
      1532625.88      6768002.68
#Sta/Elev= 30
  4580.8 2042.88  4617.6 2041.92  4647.9 2034.93  4726.3 2028.26  4794.7 2026.26
  4961.1 2026.66  4985.5 2021.71    4986 2021.21  4993.9 2021.71  4998.5 2024.37
  5003.9 2024.37  5013.3 2026.91    5058 2026.26  5123.9 2026.98  5133.5 2029.52
  5156.2 2038.98  5161.8 2039.65  5168.2 2043.58  5184.5 2048.17  5190.3 2052.27
  5196.8 2054.69  5207.3  2059.9  5223.5 2065.36    5230 2069.54  5245.6 2075.17
  5252.8 2079.93  5258.3 2081.15  5267.7 2085.42  5281.1 2086.94  5301.9  2086.8
#Mann= 6 ,-1 , 0
  4580.8     .07       0  4961.1    .035       0  4985.5    .035       0
  4993.9    .035       0    5058     .07       0  5196.8     .16       0
Bank Sta=4985.5,4993.9
XS Rating Curve= 0 ,0
Exp/Cntr=0.3,0.1

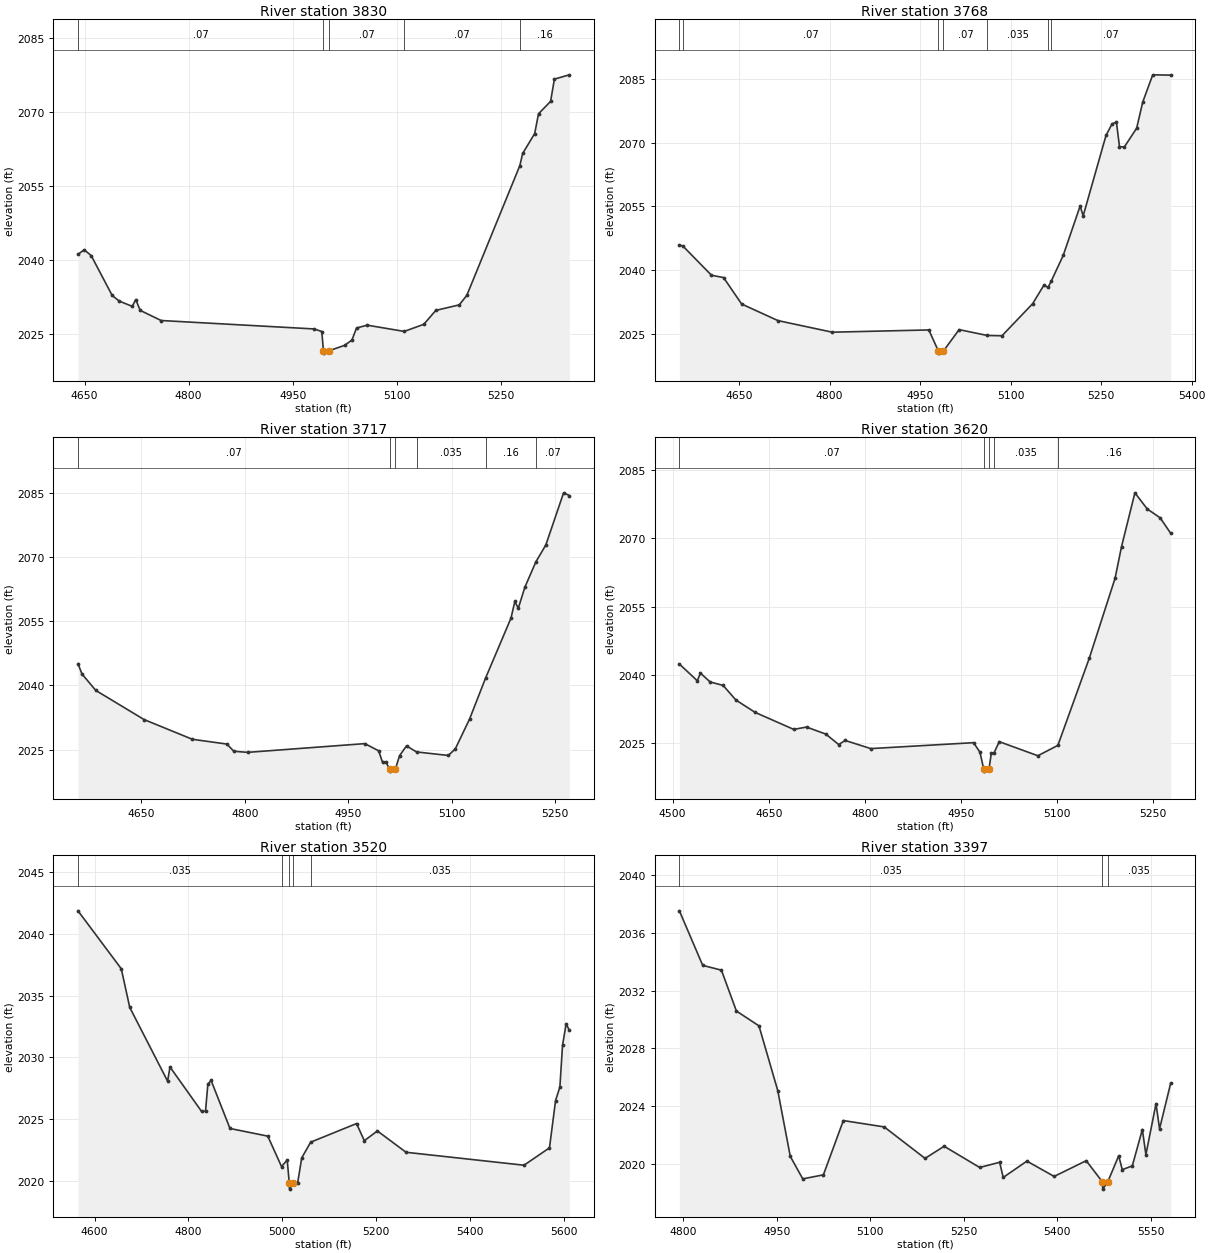
Type RM Length L Ch R = 1 ,3830    ,62,62,62
BEGIN DESCRIPTION:
Elm 74 4199
END DESCRIPTION:
XS GIS Cut Line= 3
      1531956.02      6768232.37      1532313.07       6768191.3
      1532628.81      6768043.55
#Sta/Elev= 30
  4640.6 2041.09  4649.6 2042.03  4659.7 2040.82  4689.9 2032.76    4700 2031.62
  4718.8 2030.55  4723.9 2031.92  4730.2 2029.74  4760.4 2027.68    4981 2025.97
  4991.9 2025.45  4994.3 2021.57  4994.8 2021.07  5002.7 2021.57  5024.7 2022.64
  5035.3 2023.71    5042 2026.16  5057.3 2026.74  5110.7 2025.47  5138.9 2026.91
  5156.2 2029.73    5190 2030.85  5200.9 2032.78  5277.3 2059.08  5281.4 2061.55
  5298.7 2065.58  5304.2 2069.58  5321.6  2072.1  5327.1 2076.61  5348.6 2077.48
#Mann= 5 ,-1 , 0
  4640.6     .07       0  4994.3    .035       0  5002.7     .07       0
  5110.7     .07       0  5277.3     .16       0
Bank Sta=4994.3,5002.7
XS Rating Curve= 0 ,0
Exp/Cntr=0.3,0.1

Type RM Length L Ch R = 1 ,3768    ,51,51,51
BEGIN DESCRIPTION:
Elm 74 4200
END DESCRIPTION:
XS GIS Cut Line= 3
      1531901.81      6768254.06      1532350.58      6768239.64
      1532710.68      6768178.21
#Sta/Elev= 30
    4551 2045.95  4557.1 2045.64  4604.2  2038.8  4624.2 2038.26  4654.2 2032.03
  4714.3 2028.13  4804.3  2025.4  4964.4 2025.93  4980.2 2020.97  4980.7 2020.47
  4988.6 2020.97  5014.6    2026  5061.2 2024.63  5085.6 2024.55  5136.4  2032.1
    5155 2036.44  5162.1 2035.96  5167.3 2037.43  5187.1 2043.47  5215.2 2055.12
  5220.2 2052.78  5258.1 2071.75  5268.2 2074.46  5275.3 2074.85  5280.4 2069.07
  5288.5 2069.02  5308.8 2073.41    5319 2079.62  5335.5 2085.99  5365.3 2085.92
#Mann= 7 ,-1 , 0
    4551    .035       0  4557.1     .07       0  4980.2     .07       0
  4988.6     .07       0  5061.2    .035       0  5162.1     .16       0
  5167.3     .07       0
Bank Sta=4980.2,4988.6
XS Rating Curve= 0 ,0
Exp/Cntr=0.3,0.1

Type RM Length L Ch R = 1 ,3717    ,97,97,97
BEGIN DESCRIPTION:
Elm 74 4198
END DESCRIPTION:
XS GIS Cut Line= 3
      1531919.16      6768277.94      1532361.09      6768290.17
      1532628.77       6768251.9
#Sta/Elev= 30
  4557.9 2045.07  4563.7 2042.68  4583.7 2038.84  4653.8 2032.03  4723.8 2027.43
  4773.8 2026.32  4783.8 2024.64  4803.8 2024.38  4973.9 2026.42  4993.9 2024.74
  4999.5 2022.08  5004.5 2022.08  5009.8  2020.5  5010.3    2020  5018.2  2020.5
  5024.2  2023.6  5034.3 2025.89  5048.8 2024.48  5094.9 2023.66    5105 2025.17
  5125.8 2032.18  5149.2 2041.82  5185.8 2055.71  5191.4  2059.6  5196.4 2058.02
    5206 2062.95  5221.9 2068.85  5236.3 2072.78  5262.1 2084.96  5270.4 2084.33
#Mann= 6 ,-1 , 0
  4557.9     .07       0  5009.8     .07       0  5018.2     .07       0
  5048.8    .035       0  5149.2     .16       0  5221.9     .07       0
Bank Sta=5009.8,5018.2
XS Rating Curve= 0 ,0
Exp/Cntr=0.3,0.1

Type RM Length L Ch R = 1 ,3620    ,100,100,100
BEGIN DESCRIPTION:
Elm 74 4197
END DESCRIPTION:
XS GIS Cut Line= 3
      1531916.98      6768340.87      1532405.44      6768372.82
      1532681.48      6768347.52
#Sta/Elev= 30
  4510.5 2042.39  4538.4 2038.72  4543.4 2040.38  4558.6 2038.44  4578.7  2037.7
  4598.7 2034.48  4628.8 2031.76  4688.9 2028.03  4708.9 2028.54    4739    2027
  4759.1  2024.7  4769.1  2025.6  4809.2 2023.81  4969.5 2025.11  4979.5 2023.03
  4985.3 2019.36  4985.8 2018.86  4993.7 2019.36  4997.3 2022.87  5001.5 2022.87
  5009.6 2025.33  5069.9 2022.24  5101.1 2024.52  5150.2  2043.7  5190.4 2061.25
  5200.4 2068.16  5221.3    2080  5240.6 2076.45  5260.7 2074.51  5277.2  2071.1
#Mann= 5 ,-1 , 0
  4510.5     .07       0  4985.3     .07       0  4993.7     .07       0
  5001.5    .035       0  5101.1     .16       0
Bank Sta=4985.3,4993.7
XS Rating Curve= 0 ,0
Exp/Cntr=0.3,0.1

Type RM Length L Ch R = 1 ,3520    ,123,123,123
BEGIN DESCRIPTION:
Elm 74 4196
END DESCRIPTION:
XS GIS Cut Line= 3
      1531973.42        6768419.      1532405.48       6768472.8
      1532951.08      6768750.49
#Sta/Elev= 30
  4564.6 2041.88  4656.9 2037.18    4675 2034.04  4755.7 2028.06  4760.8 2029.21
  4828.2  2025.6  4836.5 2025.62  4841.5 2027.81  4848.4 2028.12  4888.7 2024.22
  4969.3  2023.6  4998.6 2021.13  5010.7 2021.66  5015.1  2019.8  5015.6  2019.3
  5023.6  2019.8  5033.1 2019.83  5041.6 2021.83  5060.7 2023.11  5158.5 2024.62
  5175.1 2023.23    5203 2024.02  5264.1 2022.29  5515.6 2021.24  5569.9 2022.65
  5582.9 2026.49  5592.1 2027.59  5597.7 2030.96  5605.4  2032.7  5612.2  2032.2
#Mann= 5 ,-1 , 0
  4564.6    .035       0  4998.6     .07       0  5015.1     .07       0
  5023.6     .07       0  5060.7    .035       0
Bank Sta=5015.1,5023.6
XS Rating Curve= 0 ,0
Exp/Cntr=0.3,0.1

Type RM Length L Ch R = 1 ,3397    ,138,138,138
BEGIN DESCRIPTION:
Elm 74 4190
END DESCRIPTION:
XS GIS Cut Line= 3
      1532207.75      6768609.97      1532413.14      6768594.06
      1532923.95      6768872.56
#Sta/Elev= 30
    4794 2037.53  4831.4 2033.75  4861.4 2033.42  4885.4 2030.59  4921.6 2029.56
  4951.7 2025.08  4971.8 2020.52  4991.8 2018.96  5024.9 2019.24  5056.9    2023
  5122.4 2022.56  5187.9 2020.38  5218.5 2021.22  5275.5 2019.75  5307.5 2020.11
  5313.2 2019.06  5351.2 2020.19  5394.9 2019.13  5446.3 2020.22  5472.3 2018.75
  5472.8 2018.25  5480.8 2018.75  5498.4 2020.56  5504.1  2019.6  5520.2 2019.86
  5536.3 2022.38    5542 2020.64  5558.2 2024.17  5563.9 2022.43  5581.8  2025.6
#Mann= 3 ,-1 , 0
    4794    .035       0  5472.3    .035       0  5480.8    .035       0
Bank Sta=5472.3,5480.8
XS Rating Curve= 0 ,0
Exp/Cntr=0.3,0.1

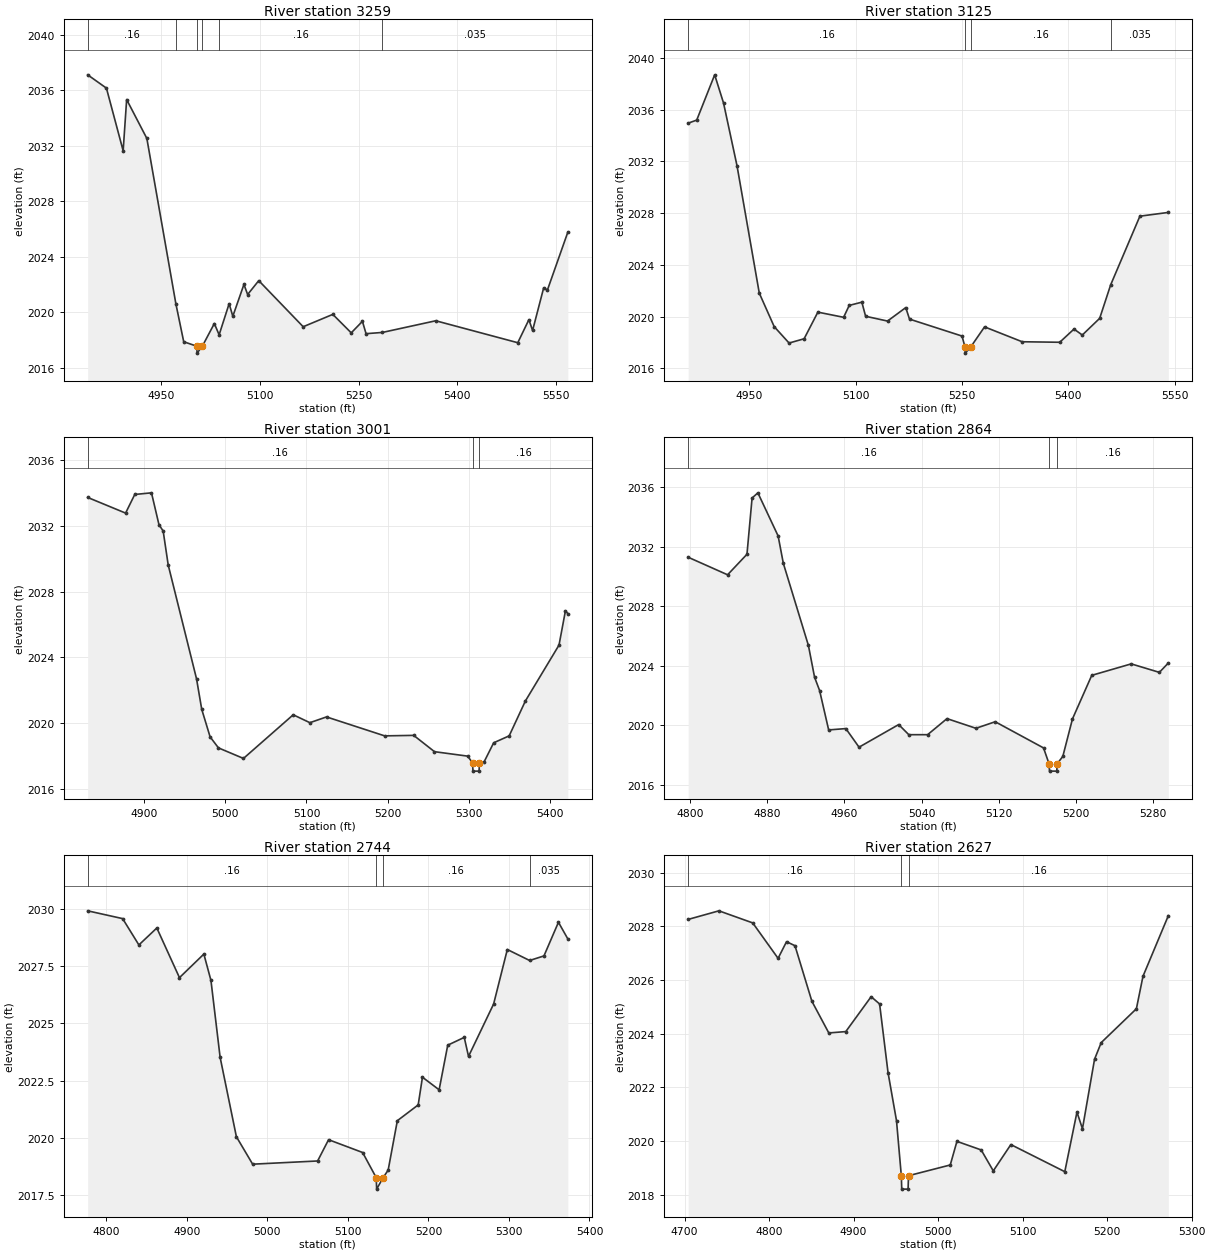
Type RM Length L Ch R = 1 ,3259    ,134,134,134
BEGIN DESCRIPTION:
Elm 74 4191
END DESCRIPTION:
XS GIS Cut Line= 3
      1532303.31      6768772.71      1532455.23      6768717.91
      1532965.18      6768968.05
#Sta/Elev= 30
  4838.5  2037.1    4867 2036.14  4892.4 2031.63  4897.7 2035.32  4928.4 2032.52
  4972.5 2020.61  4984.4 2017.88  5004.2 2017.56  5004.7 2017.06  5012.7 2017.56
  5030.9 2019.19  5038.2 2018.38  5053.4 2020.62    5059 2019.71  5075.9 2022.01
  5081.5 2021.28  5098.4 2022.28  5165.9 2018.96  5210.9 2019.85  5238.9 2018.52
  5255.9 2019.35  5261.4 2018.46  5286.2 2018.55  5367.3 2019.39  5491.9 2017.81
  5508.8 2019.47  5514.4 2018.69  5531.3 2021.77  5536.9  2021.6    5568 2025.78
#Mann= 6 ,-1 , 0
  4838.5     .16       0  4972.5    .035       0  5004.2    .035       0
  5012.7    .035       0  5038.2     .16       0  5286.2    .035       0
Bank Sta=5004.2,5012.7
XS Rating Curve= 0 ,0
Exp/Cntr=0.3,0.1

Type RM Length L Ch R = 1 ,3125    ,124,124,124
BEGIN DESCRIPTION:
Elm 74 4192
END DESCRIPTION:
XS GIS Cut Line= 3
      1532379.26      6768876.88      1532509.16      6768836.28
       1533019.4      6769015.78
#Sta/Elev= 30
  4863.9 2034.96    4876  2035.2  4901.3  2038.7  4913.8 2036.52  4932.8 2031.67
  4964.2 2021.82  4985.2 2019.23  5006.2 2017.96  5027.4 2018.29  5046.8 2020.35
  5083.1 2019.95    5091 2020.87  5108.8 2021.12  5114.1 2020.03    5145 2019.66
  5170.7  2020.7    5176 2019.81    5250  2018.5  5254.1 2017.68  5254.6 2017.18
  5262.6 2017.68  5281.8 2019.21  5334.8 2018.06  5387.8 2018.02  5407.9 2019.04
  5419.6 2018.58  5444.1 2019.87  5459.6 2022.46  5500.8 2027.77  5540.9 2028.06
#Mann= 4 ,-1 , 0
  4863.9     .16       0  5254.1     .07       0  5262.6     .16       0
  5459.6    .035       0
Bank Sta=5254.1,5262.6
XS Rating Curve= 0 ,0
Exp/Cntr=0.3,0.1

Type RM Length L Ch R = 1 ,3001    ,137,137,137
BEGIN DESCRIPTION:
Elm 74 4193
END DESCRIPTION:
XS GIS Cut Line= 3
      1532398.76       6768985.4      1532563.14      6768944.06
      1532975.65      6769033.07
#Sta/Elev= 30
  4830.5 2033.71  4877.2 2032.76  4888.5 2033.89  4909.1 2033.99  4918.3 2032.06
  4923.5 2031.67  4929.7 2029.61  4964.6  2022.7    4971 2020.85  4981.3 2019.18
  4991.6 2018.51  5022.4 2017.87  5083.7 2020.52  5104.2 2020.04  5124.7 2020.39
  5196.3 2019.24  5232.1 2019.27  5257.7 2018.28  5298.6 2018.01  5304.6  2017.6
  5305.1  2017.1  5312.6  2017.1  5313.1  2017.6    5319 2017.68  5330.6 2018.82
  5349.7 2019.24  5369.7 2021.36  5411.1 2024.75    5419 2026.83    5422 2026.66
#Mann= 3 ,-1 , 0
  4830.5     .16       0  5304.6     .07       0  5313.1     .16       0
Bank Sta=5304.6,5313.1
XS Rating Curve= 0 ,0
Exp/Cntr=0.3,0.1

Type RM Length L Ch R = 1 ,2864    ,120,120,120
BEGIN DESCRIPTION:
Elm 74 4194
END DESCRIPTION:
XS GIS Cut Line= 3
      1532465.99       6769102.6       1532658.8      6769042.04
      1532954.32      6769054.85
#Sta/Elev= 30
  4797.9  2031.3  4838.8 2030.12  4858.9  2031.5  4864.2 2035.28  4870.2 2035.63
  4891.2 2032.73  4896.6 2030.89  4922.6 2025.37    4929 2023.23  4934.2 2022.34
  4943.6 2019.69  4961.4 2019.78  4975.1 2018.53  5016.2 2020.05  5026.7 2019.37
  5046.2 2019.37  5066.3 2020.45  5096.3  2019.8  5116.3 2020.24  5166.4 2018.48
  5172.1 2017.42  5172.6 2016.92  5180.1 2016.92  5180.6 2017.42  5186.4 2017.91
  5196.4 2020.43  5216.4 2023.36  5257.3 2024.13  5286.5 2023.56  5295.8 2024.19
#Mann= 3 ,-1 , 0
  4797.9     .16       0  5172.1     .07       0  5180.6     .16       0
Bank Sta=5172.1,5180.6
XS Rating Curve= 0 ,0
Exp/Cntr=0.3,0.1

Type RM Length L Ch R = 1 ,2744    ,117,117,117
BEGIN DESCRIPTION:
Elm 74 4195
END DESCRIPTION:
XS GIS Cut Line= 3
      1532492.03      6769174.21      1532713.18      6769144.04
      1533066.09      6769022.66
#Sta/Elev= 30
  4776.8 2029.92  4820.2 2029.58  4840.4 2028.43  4862.7 2029.17  4890.8    2027
  4921.1 2028.03  4929.9 2026.88  4941.3 2023.52  4961.5 2020.05  4981.7 2018.85
  5062.4 2018.99    5076 2019.92  5118.3 2019.36  5135.2 2018.26  5135.7 2017.76
  5143.7 2018.26    5150 2018.59  5161.4 2020.75  5187.3 2021.44  5192.6 2022.65
  5213.3  2022.1    5224 2024.05  5244.5 2024.39  5249.8 2023.56    5281 2025.85
    5298 2028.23  5325.7 2027.75  5343.5 2027.95  5361.5 2029.42  5373.2 2028.69
#Mann= 4 ,-1 , 0
  4776.8     .16       0  5135.2     .07       0  5143.7     .16       0
  5325.7    .035       0
Bank Sta=5135.2,5143.7
XS Rating Curve= 0 ,0
Exp/Cntr=0.3,0.1

Type RM Length L Ch R = 1 ,2627    ,69,69,69
BEGIN DESCRIPTION:
Elm 74 4189
END DESCRIPTION:
XS GIS Cut Line= 3
      1532498.63      6769237.14       1532794.2      6769228.33
      1533004.22      6769054.85
#Sta/Elev= 30
  4704.3 2028.26  4740.7 2028.58  4780.7 2028.13  4810.7 2026.81  4820.7 2027.43
  4830.7 2027.28  4850.7 2025.21  4870.7 2024.03  4890.8 2024.08  4920.8 2025.38
  4930.8 2025.11  4940.8 2022.55  4950.8 2020.76  4956.5 2018.71    4957 2018.21
  4964.5 2018.21    4965 2018.71  5014.4 2019.11  5022.3 2019.99    5051 2019.67
  5065.3 2018.89  5086.1 2019.87  5149.9 2018.86  5164.3 2021.08  5170.8 2020.46
  5185.1 2023.05    5193 2023.67  5234.6 2024.93  5242.4 2026.14  5272.4  2028.4
#Mann= 3 ,-1 , 0
  4704.3     .16       0  4956.5     .07       0    4965     .16       0
Bank Sta=4956.5,4965
XS Rating Curve= 0 ,0
Exp/Cntr=0.3,0.1