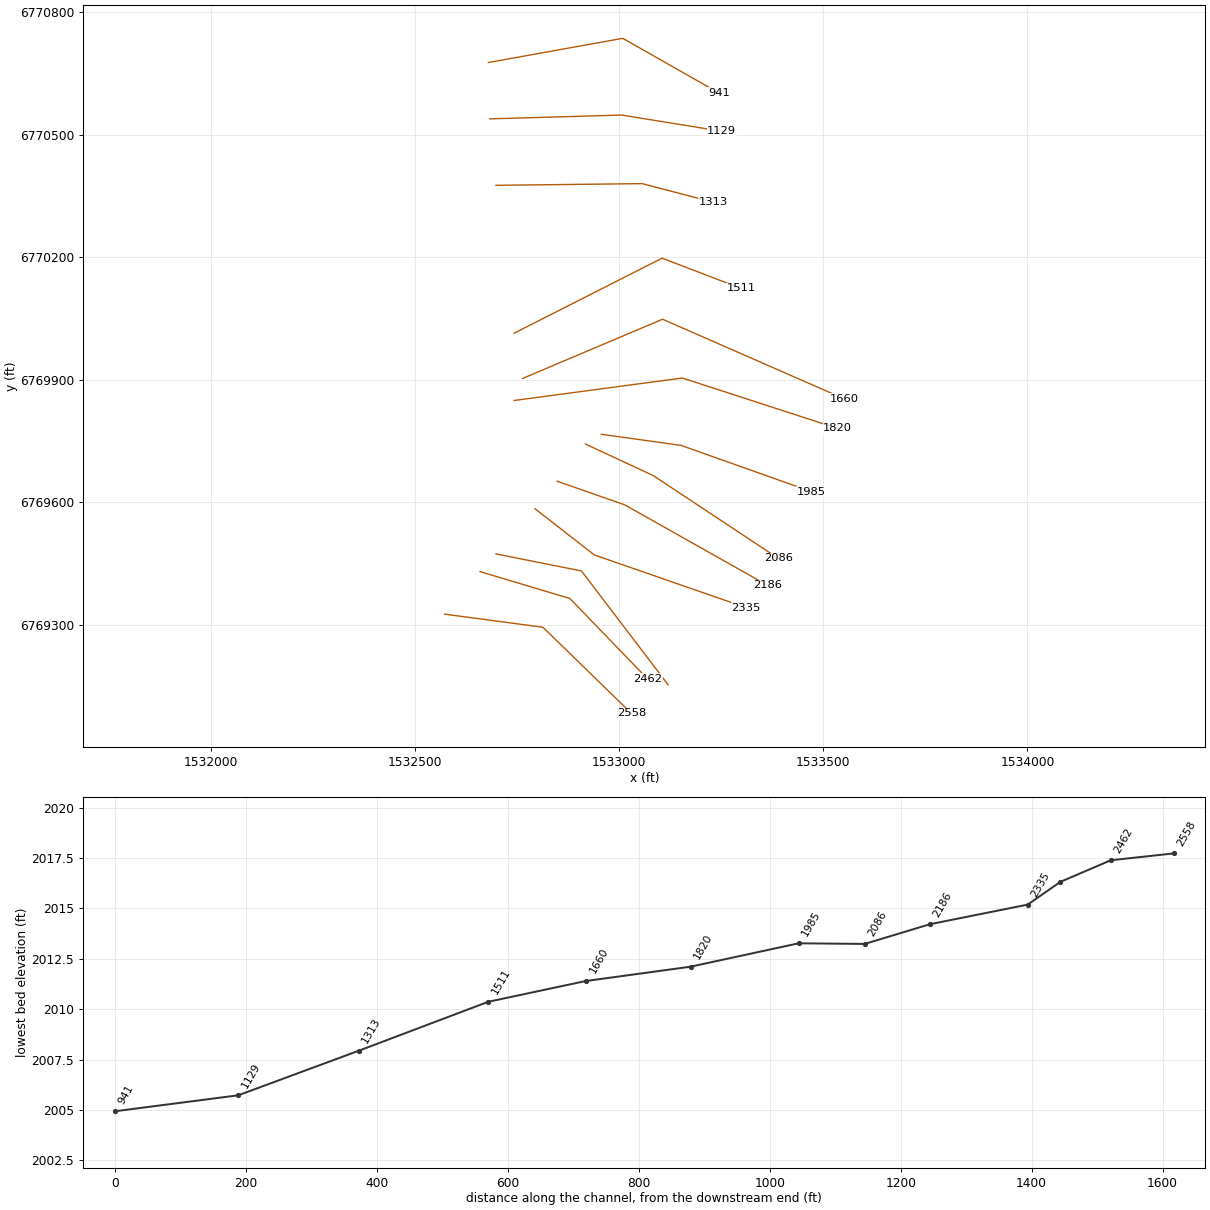
HEC-RAS study Elm 74.prj: Elm 74 Base Level Engineering

--- Elm 74.g01 (geometry) --- (continued)

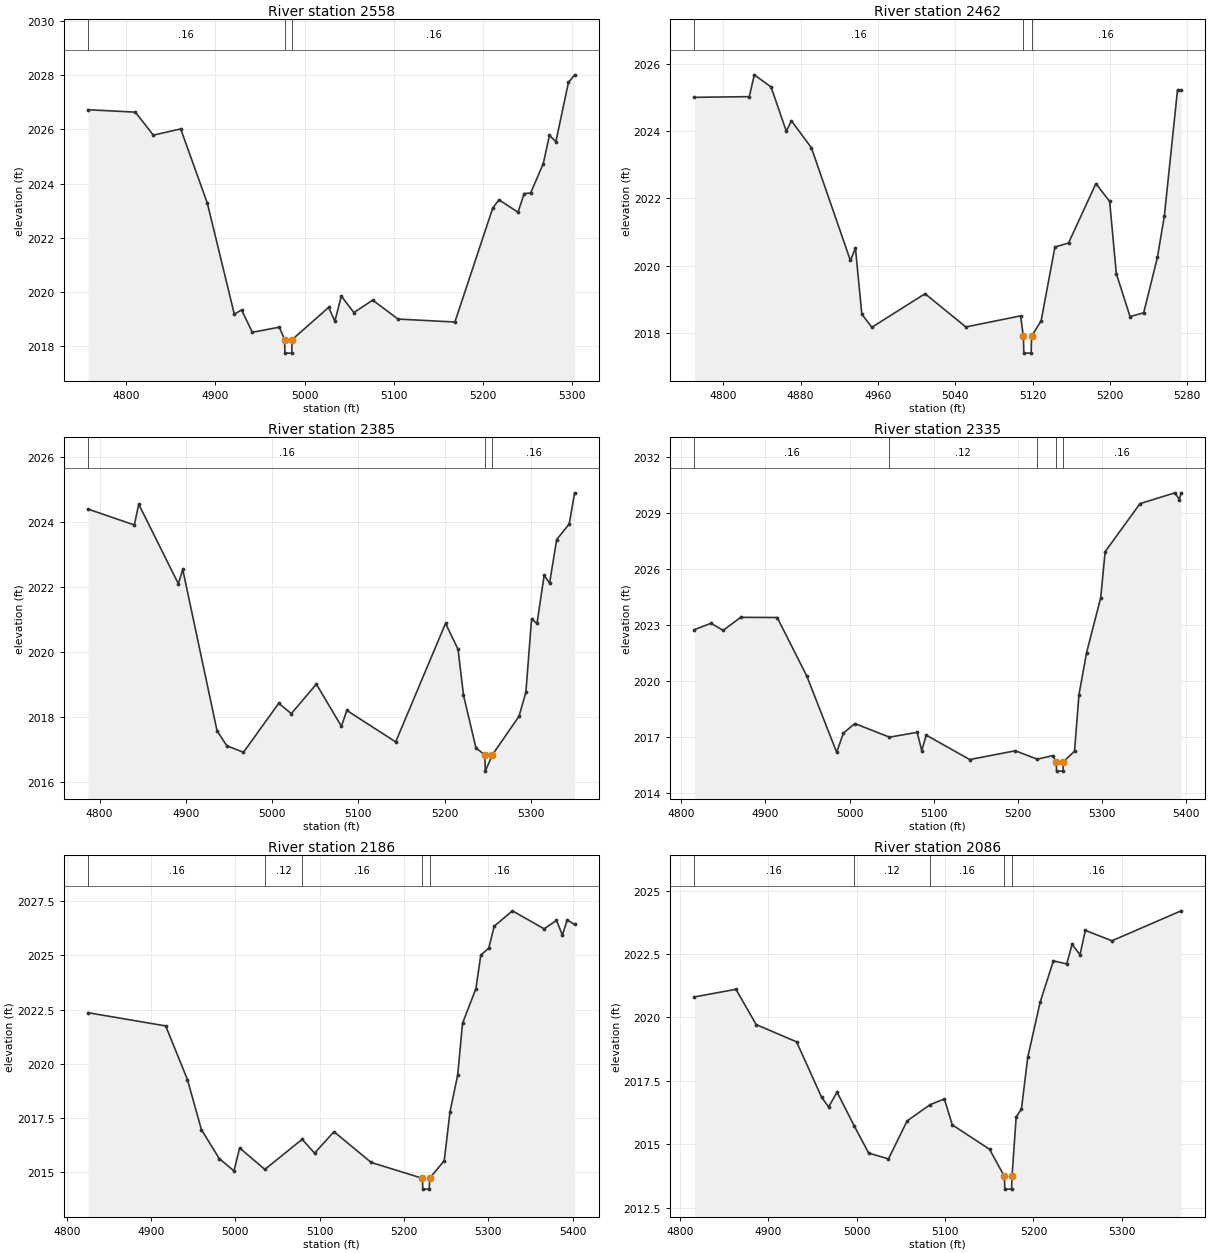
Type RM Length L Ch R = 1 ,2558    ,96,96,96
BEGIN DESCRIPTION:
Elm 74 4188
END DESCRIPTION:
XS GIS Cut Line= 3
       1532572.4      6769326.11      1532813.18      6769294.04
      1533029.98      6769083.08
#Sta/Elev= 30
  4757.1 2026.73  4810.2 2026.64  4830.3 2025.79    4861 2026.02  4890.9 2023.27
  4921.1 2019.17  4929.2 2019.33  4941.3  2018.5  4971.6 2018.69  4977.4 2018.23
  4977.9 2017.73  4985.4 2017.73  4985.9 2018.23  5026.8 2019.42  5033.8 2018.91
    5041 2019.84  5055.1 2019.23  5076.2 2019.69  5104.5 2018.99  5168.3 2018.88
  5210.7 2023.09  5217.7  2023.4    5239 2022.94    5246 2023.63  5253.2 2023.65
  5267.3 2024.73  5274.3 2025.78  5281.5 2025.55  5295.6 2027.74  5302.5 2028.02
#Mann= 3 ,-1 , 0
  4757.1     .16       0  4977.4     .07       0  4985.9     .16       0
Bank Sta=4977.4,4985.9
XS Rating Curve= 0 ,0
Exp/Cntr=0.3,0.1

Type RM Length L Ch R = 1 ,2462    ,77,77,77
BEGIN DESCRIPTION:
Elm 74 4187
END DESCRIPTION:
XS GIS Cut Line= 3
      1532659.15      6769430.29      1532879.23      6769364.49
      1533069.32      6769167.71
#Sta/Elev= 30
  4770.3 2025.01    4827 2025.03  4832.2 2025.68  4849.5 2025.32  4865.3    2024
  4870.6 2024.31  4891.2 2023.51  4931.6 2020.15  4936.8 2020.52  4943.4 2018.55
  4953.8 2018.16  5008.8 2019.16    5051 2018.17  5107.6  2018.5  5110.5 2017.89
    5111 2017.39  5118.5 2017.39    5119 2017.89  5128.9 2018.36  5143.1 2020.55
  5157.2 2020.67  5185.5 2022.44  5199.7 2021.91  5206.6 2019.76  5220.8 2018.48
  5234.9 2018.59  5249.1 2020.24  5256.3 2021.48  5269.9 2025.23  5273.6 2025.23
#Mann= 3 ,-1 , 0
  4770.3     .16       0  5110.5     .07       0    5119     .16       0
Bank Sta=5110.5,5119
XS Rating Curve= 0 ,0
Exp/Cntr=0.3,0.1

Type RM Length L Ch R = 1 ,2385    ,50,50,50
BEGIN DESCRIPTION:
Elm 74 4186
END DESCRIPTION:
XS GIS Cut Line= 3
      1532698.26      6769473.68      1532907.54      6769431.95
      1533119.96      6769153.02
#Sta/Elev= 30
  4786.6 2024.39  4840.3  2023.9  4845.4 2024.54  4891.3 2022.09  4896.4 2022.53
  4936.2 2017.56  4947.5  2017.1  4966.8  2016.9  5007.7 2018.41  5022.2 2018.09
  5051.3    2019  5080.3  2017.7  5086.6 2018.19  5143.2 2017.22    5201 2020.87
  5215.5 2020.07  5221.8 2018.66  5236.3 2017.03  5246.6 2016.82  5247.1 2016.32
  5255.2 2016.82  5286.2 2018.01  5294.1 2018.75  5300.7    2021    5307 2020.87
  5315.3 2022.35  5321.6 2022.11  5329.8 2023.45  5344.3 2023.93  5350.6 2024.89
#Mann= 3 ,-1 , 0
  4786.6     .16       0  5246.6     .07       0  5255.2     .16       0
Bank Sta=5246.6,5255.2
XS Rating Curve= 0 ,0
Exp/Cntr=0.3,0.1

Type RM Length L Ch R = 1 ,2335    ,149,149,149
BEGIN DESCRIPTION:
Elm 74 4185
END DESCRIPTION:
XS GIS Cut Line= 3
      1532793.69      6769584.38      1532939.01       6769471.2
      1533311.12      6769341.99
#Sta/Elev= 30
  4815.8 2022.77  4835.4 2023.11  4849.9 2022.73  4870.7 2023.43  4914.1 2023.42
  4949.4 2020.27  4984.7  2016.2  4992.8 2017.23  5006.3 2017.74  5047.5 2017.01
  5080.4 2017.27  5085.8 2016.29  5091.1 2017.12  5142.8 2015.81  5196.9 2016.28
    5223 2015.83  5241.4 2016.02  5245.5 2015.69    5246 2015.19  5253.6 2015.19
  5254.1 2015.69  5267.3 2016.26  5272.6 2019.29  5281.6 2021.53  5298.4 2024.48
  5303.7 2026.95  5345.1 2029.52  5386.5  2030.1  5391.8 2029.74  5393.9  2030.1
#Mann= 5 ,-1 , 0
  4815.8     .16       0  5047.5     .12       0    5223     .16       0
  5245.5     .07       0  5254.1     .16       0
Bank Sta=5245.5,5254.1
XS Rating Curve= 0 ,0
Exp/Cntr=0.3,0.1

Type RM Length L Ch R = 1 ,2186    ,100,100,100
BEGIN DESCRIPTION:
Elm 74 4184
END DESCRIPTION:
XS GIS Cut Line= 3
      1532848.01      6769651.62      1533013.16      6769594.05
      1533363.73       6769396.5
#Sta/Elev= 30
  4825.1 2022.36  4917.3 2021.75  4943.1 2019.27  4959.6 2016.97  4980.8 2015.63
  4998.3 2015.06    5005 2016.12  5034.9 2015.13  5079.2 2016.52  5093.9 2015.88
  5116.9 2016.87  5161.1 2015.45  5221.8 2014.72  5222.3 2014.22  5229.9 2014.22
  5230.4 2014.72  5247.7 2015.53  5254.6  2017.8  5263.7 2019.49  5269.4 2021.87
  5285.3 2023.47  5291.1 2025.02  5300.6 2025.34    5307 2026.35  5328.6 2027.06
  5366.2 2026.23  5380.9 2026.62  5387.9 2025.94  5393.6 2026.64  5402.4 2026.43
#Mann= 5 ,-1 , 0
  4825.1     .16       0  5034.9     .12       0  5079.2     .16       0
  5221.8     .07       0  5230.4     .16       0
Bank Sta=5221.8,5230.4
XS Rating Curve= 0 ,0
Exp/Cntr=0.3,0.1

Type RM Length L Ch R = 1 ,2086    ,101,101,101
BEGIN DESCRIPTION:
Elm 74 4182
END DESCRIPTION:
XS GIS Cut Line= 3
      1532917.44      6769742.77      1533083.61      6769665.39
      1533389.59      6769462.75
#Sta/Elev= 30
  4816.7 2020.81  4863.6 2021.11  4886.5 2019.72  4932.2 2019.04  4960.6 2016.85
  4968.4 2016.48    4978 2017.06  4997.2 2015.74  5013.7 2014.66  5036.1 2014.43
  5057.2 2015.93  5083.4 2016.57  5099.3 2016.79  5108.3 2015.77  5150.4 2014.81
  5167.2 2013.74  5167.7 2013.24  5175.3 2013.24  5175.8 2013.74  5180.5 2016.08
  5186.5  2016.4  5193.6 2018.43  5207.6  2020.6  5222.6 2022.23  5237.7 2022.11
  5243.7 2022.88  5252.7 2022.47  5258.7 2023.43  5288.8 2023.02    5367  2024.2
#Mann= 5 ,-1 , 0
  4816.7     .16       0  4997.2     .12       0  5083.4     .16       0
  5167.2     .07       0  5175.8     .16       0
Bank Sta=5167.2,5175.8
XS Rating Curve= 0 ,0
Exp/Cntr=0.3,0.1

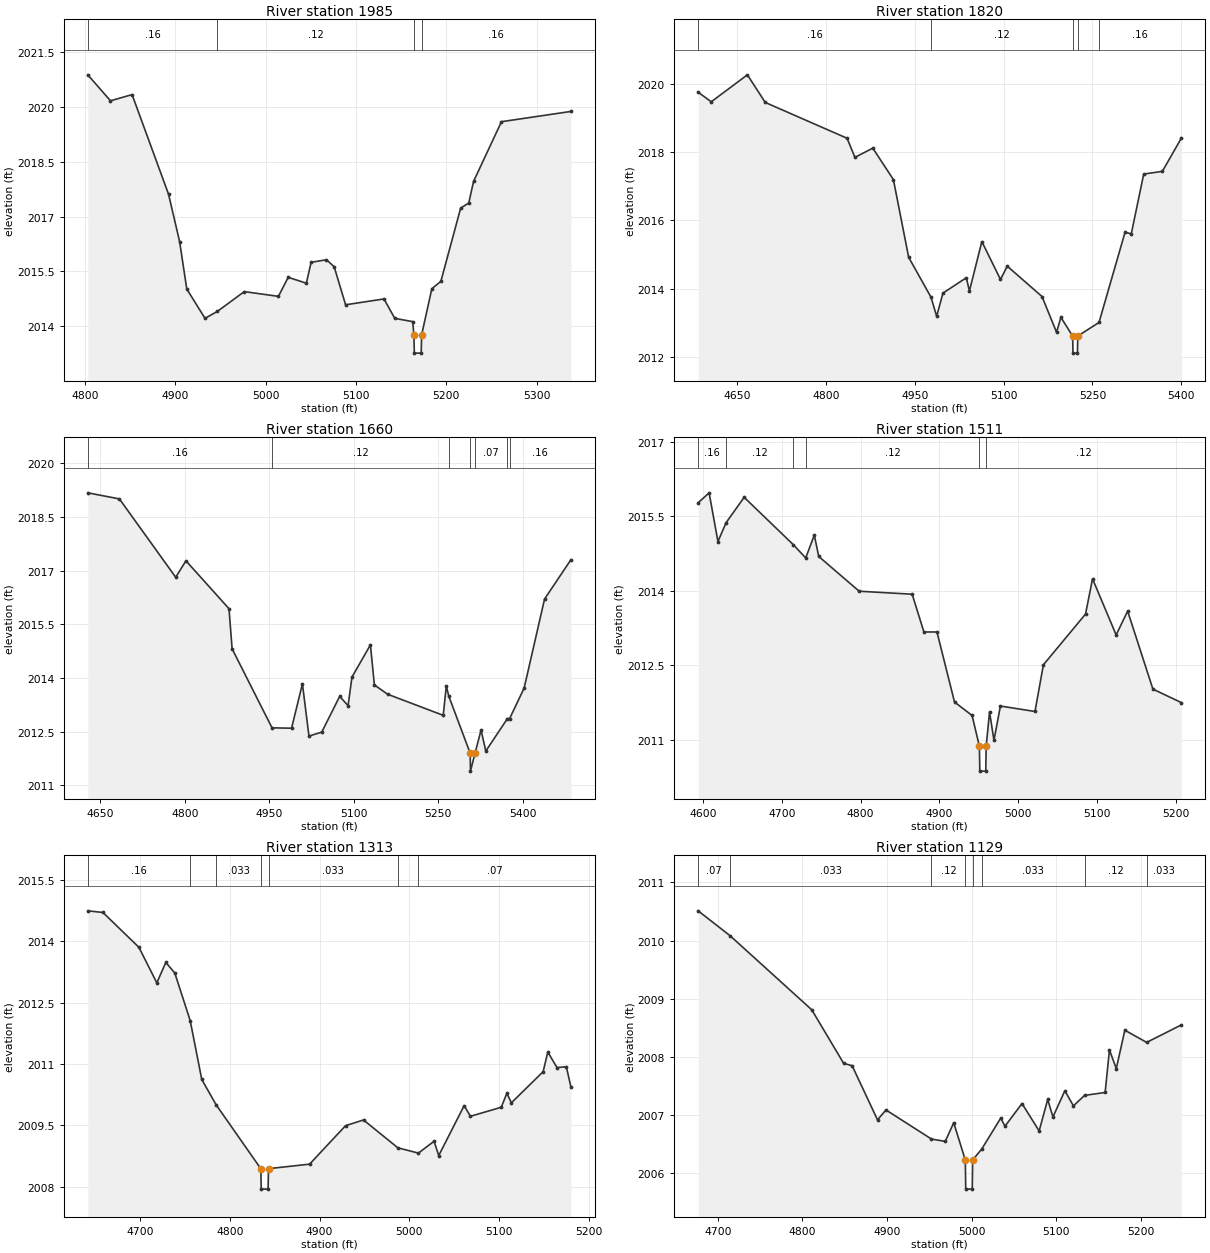
Type RM Length L Ch R = 1 ,1985    ,165,165,165
BEGIN DESCRIPTION:
Elm 74 4183
END DESCRIPTION:
XS GIS Cut Line= 3
      1532956.45      6769766.66      1533151.46      6769739.46
       1533470.1      6769626.42
#Sta/Elev= 30
  4803.1 2020.87  4828.2 2020.16  4852.1 2020.33  4892.5 2017.61  4904.8 2016.31
  4912.7 2015.02  4932.9 2014.22  4946.6 2014.41  4976.4 2014.95  5014.2 2014.82
    5025 2015.34  5045.1 2015.18  5050.4 2015.75  5067.4 2015.82  5075.9 2015.63
  5088.6 2014.59  5131.1 2014.75    5143 2014.22  5162.9 2014.13  5164.2 2013.77
  5164.7 2013.27  5172.3 2013.27  5172.8 2013.77  5184.1 2015.03  5194.1 2015.23
    5216 2017.23    5225 2017.37  5230.3 2017.96  5261.2 2019.59  5338.1 2019.87
#Mann= 4 ,-1 , 0
  4803.1     .16       0  4946.6     .12       0  5164.2     .07       0
  5172.8     .16       0
Bank Sta=5164.2,5172.8
XS Rating Curve= 0 ,0
Exp/Cntr=0.3,0.1

Type RM Length L Ch R = 1 ,1820    ,160,160,160
BEGIN DESCRIPTION:
Elm 74 4181
END DESCRIPTION:
XS GIS Cut Line= 3
      1532742.65      6769849.47       1533154.8      6769904.46
      1533535.32      6769780.84
#Sta/Elev= 30
  4584.2 2019.76  4606.3 2019.48  4667.3 2020.27  4697.5 2019.46  4835.7 2018.41
  4848.9 2017.85  4879.1 2018.12  4913.9  2017.2  4939.7 2014.92  4977.4 2013.75
    4987 2013.19  4997.6 2013.87  5037.1 2014.32  5042.3 2013.93  5063.3 2015.38
  5094.8 2014.27  5106.2 2014.66  5164.9 2013.77  5189.5 2012.72  5196.8 2013.16
  5216.7 2012.61  5217.2 2012.11  5224.8 2012.11  5225.3 2012.61  5261.2 2013.01
  5305.1 2015.65  5315.7 2015.61  5336.7 2017.36  5368.2 2017.44  5400.1 2018.41
#Mann= 5 ,-1 , 0
  4584.2     .16       0  4977.4     .12       0  5216.7     .07       0
  5225.3     .12       0  5261.2     .16       0
Bank Sta=5216.7,5225.3
XS Rating Curve= 0 ,0
Exp/Cntr=0.3,0.1

Type RM Length L Ch R = 1 ,1660    ,149,149,149
BEGIN DESCRIPTION:
Elm 74 4179
END DESCRIPTION:
XS GIS Cut Line= 3
      1532763.37      6769903.38      1533106.22       6770048.5
      1533551.15      6769853.48
#Sta/Elev= 30
  4627.7 2019.18  4683.8 2019.01  4783.8 2016.82    4802 2017.28  4878.5 2015.94
    4884 2014.82  4954.9 2012.61  4989.6  2012.6  5008.9 2013.84  5020.5 2012.38
  5043.2 2012.49  5075.1 2013.49    5090 2013.23  5096.9 2014.03  5129.7 2014.93
  5136.7 2013.81  5160.1 2013.55    5259 2012.96  5264.5 2013.78  5268.8  2013.5
  5306.9  2011.9  5307.4  2011.4  5315.5  2011.9  5326.2 2012.55  5334.6 2011.96
  5373.1 2012.87    5377 2012.87  5402.7 2013.72    5439 2016.21  5485.8 2017.31
#Mann= 7 ,-1 , 0
  4627.7     .16       0  4954.9     .12       0  5268.8     .07       0
  5306.9     .07       0  5315.5     .07       0  5373.1     .12       0
    5377     .16       0
Bank Sta=5306.9,5315.5
XS Rating Curve= 0 ,0
Exp/Cntr=0.3,0.1

Type RM Length L Ch R = 1 ,1511    ,198,198,198
BEGIN DESCRIPTION:
Elm 74 4178
END DESCRIPTION:
XS GIS Cut Line= 3
      1532742.62      6770014.19      1533105.06      6770198.02
      1533298.58      6770123.98
#Sta/Elev= 30
  4593.6 2015.77  4607.5 2015.97  4618.7 2014.99  4629.1 2015.37    4652 2015.88
  4714.2 2014.93  4730.2 2014.66  4741.1 2015.12  4746.7 2014.69  4798.1 2013.99
  4865.4 2013.93  4880.3 2013.17  4896.9 2013.17  4919.2 2011.76  4941.5 2011.49
  4950.8 2010.87  4951.3 2010.37  4958.9 2010.37  4959.4 2010.87  4963.7 2011.56
  4969.3 2010.99  4977.5 2011.68  5021.4 2011.57  5032.1 2012.51  5085.6 2013.53
  5094.5 2014.24  5124.5 2013.11  5139.1 2013.59  5171.2 2012.02  5207.2 2011.75
#Mann= 6 ,-1 , 0
  4593.6     .16       0  4629.1     .12       0  4714.2     .16       0
  4730.2     .12       0  4950.8     .07       0  4959.4     .12       0
Bank Sta=4950.8,4959.4
XS Rating Curve= 0 ,0
Exp/Cntr=0.3,0.1

Type RM Length L Ch R = 1 ,1313    ,184,184,184
BEGIN DESCRIPTION:
Elm 74 4177
END DESCRIPTION:
XS GIS Cut Line= 3
      1532698.19      6770376.46      1533056.07      6770380.58
      1533229.95      6770335.24
#Sta/Elev= 30
  4642.1 2014.74  4658.9  2014.7  4698.9 2013.85  4718.9 2012.98  4728.9 2013.48
  4738.9 2013.22    4756 2012.06  4768.9 2010.62  4784.9    2010  4834.6 2008.44
  4835.1 2007.94  4842.7 2007.94  4843.2 2008.44  4888.9 2008.55  4928.9 2009.49
  4948.9 2009.63  4987.1 2008.95    5010 2008.82  5027.4 2009.11  5032.6 2008.76
  5060.9 2009.98  5067.9 2009.72  5102.2 2009.94  5108.4 2010.28  5113.5 2010.05
  5148.8 2010.81    5154 2011.29  5164.2 2010.91  5174.6 2010.93  5179.7 2010.44
#Mann= 7 ,-1 , 0
  4642.1     .16       0    4756     .07       0  4784.9    .033       0
  4834.6     .07       0  4843.2    .033       0  4987.1     .12       0
    5010     .07       0
Bank Sta=4834.6,4843.2
XS Rating Curve= 0 ,0
Exp/Cntr=0.3,0.1

Type RM Length L Ch R = 1 ,1129    ,188,188,188
BEGIN DESCRIPTION:
Elm 74 4176
END DESCRIPTION:
XS GIS Cut Line= 3
      1532683.05      6770539.22      1533006.22      6770548.51
      1533250.84      6770508.96
#Sta/Elev= 30
  4676.7 2010.51  4714.6 2010.08    4811 2008.81  4848.7 2007.89  4858.7 2007.85
  4888.7 2006.92  4898.7 2007.09  4952.5 2006.59  4968.8 2006.55  4978.8 2006.87
  4992.5 2006.23    4993 2005.73  5000.7 2005.73  5001.2 2006.23    5012 2006.42
  5034.4 2006.95  5039.4 2006.81  5059.5  2007.2  5079.8 2006.73  5089.9 2007.27
  5096.1 2006.97  5110.2 2007.42  5120.3 2007.16  5133.5 2007.34  5157.8 2007.39
  5162.9 2008.12    5171  2007.8  5181.1 2008.46  5206.9 2008.25  5247.8 2008.55
#Mann= 8 ,-1 , 0
  4676.7     .07       0  4714.6    .033       0  4952.5     .12       0
  4992.5     .07       0  5001.2     .12       0    5012    .033       0
  5133.5     .12       0  5206.9    .033       0
Bank Sta=4992.5,5001.2
XS Rating Curve= 0 ,0
Exp/Cntr=0.3,0.1

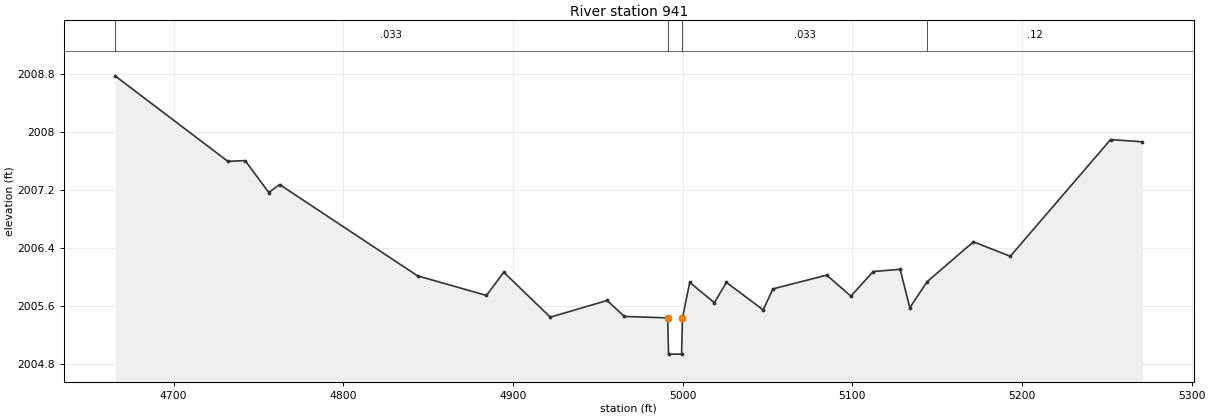
Type RM Length L Ch R = 1 ,941     ,0,0,0
BEGIN DESCRIPTION:
Elm 74 4175
END DESCRIPTION:
XS GIS Cut Line= 3
      1532679.54       6770677.2      1533008.75      6770736.45
      1533244.37      6770602.57
#Sta/Elev= 30
  4665.5 2008.78    4732  2007.6  4742.2 2007.61  4756.1 2007.17  4762.5 2007.28
  4843.8 2006.02  4884.4 2005.75  4894.6 2006.07    4922 2005.45  4955.5 2005.68
  4965.7 2005.46  4991.2 2005.44  4991.7 2004.94  4999.4 2004.94  4999.9 2005.44
  5004.2 2005.93  5018.7 2005.65  5025.8 2005.93  5047.5 2005.55  5053.2 2005.84
  5084.9 2006.03  5099.2 2005.74  5112.3 2006.08  5128.2 2006.11  5133.9 2005.58
  5144.1 2005.94  5171.4 2006.49  5193.1 2006.29  5252.2  2007.9    5271 2007.87
#Mann= 4 ,-1 , 0
  4665.5    .033       0  4991.2    .033       0  4999.9    .033       0
  5144.1     .12       0
Bank Sta=4991.2,4999.9
XS Rating Curve= 0 ,0
Exp/Cntr=0.3,0.1

Chan Stop Cuts=-1
Use User Specified Reach Order=0
Composite Channel Slope=5