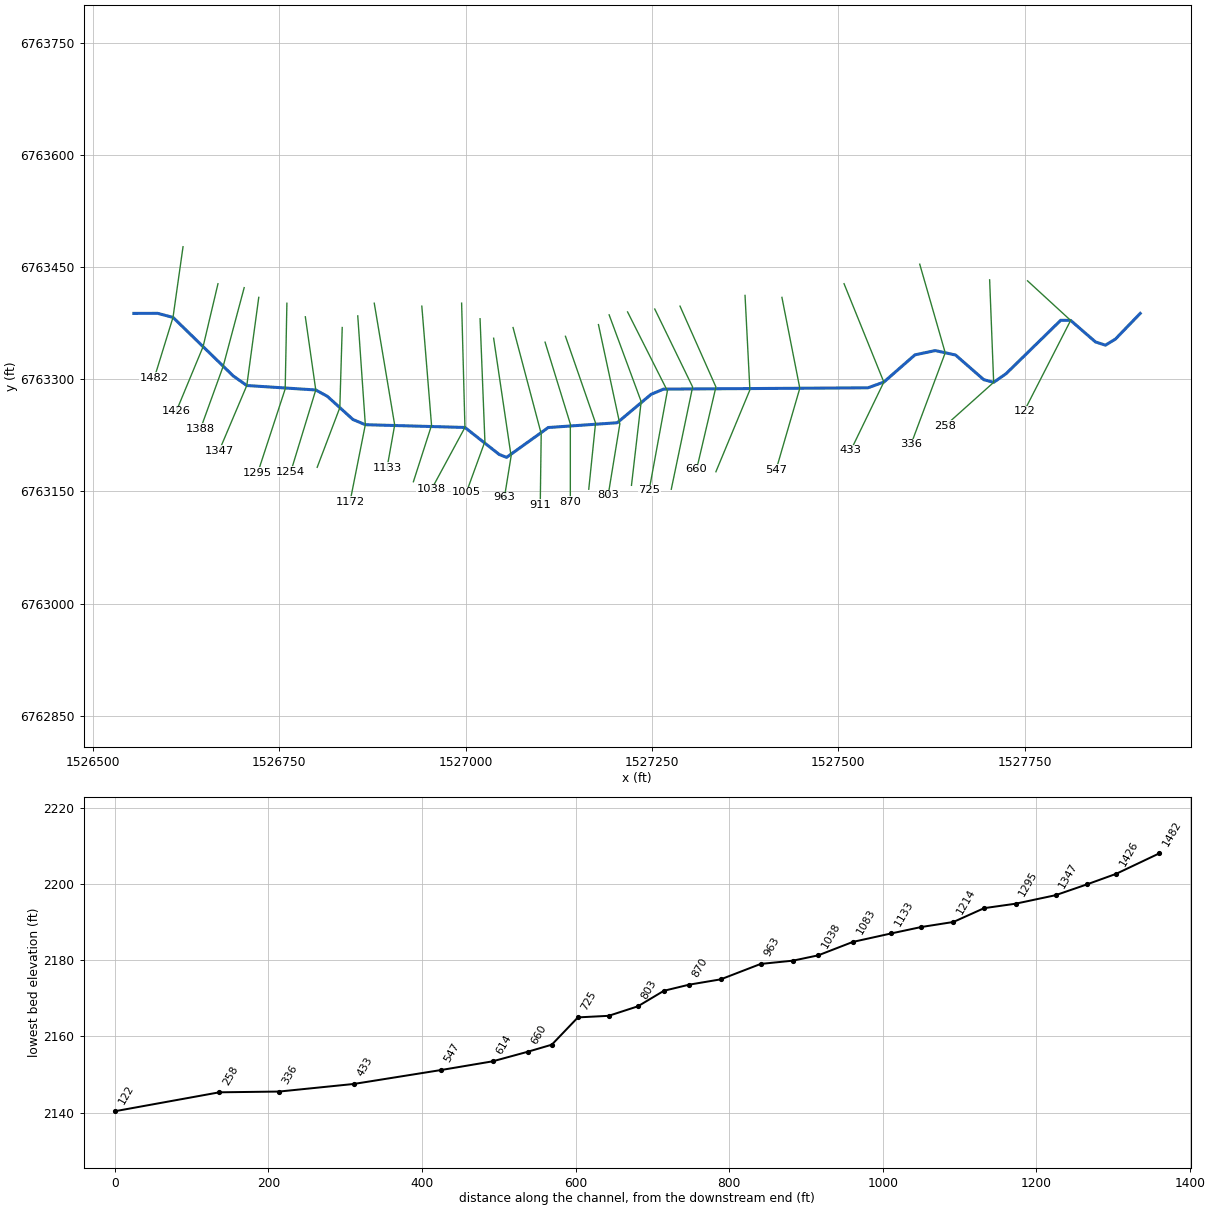
--- Elm 75.prj (project) ---

Proj Title=Elm 75 Base Level Engineering
Current Plan=p01
Default Exp/Contr=0.3,0.1
English Units
Geom File=g01
Flow File=f01
Plan File=p01
BEGIN DESCRIPTION:
Elm 75
END DESCRIPTION:

--- Elm 75.p01 (plan) ---

Plan Title=Multiple Run
Short Identifier=Multiple
Geom File=g01
Flow File=f01
Subcritical Flow
K Sum by GR= 0
Std Step Tol= 0.01
Critical Tol= 0.01
Num of Std Step Trials= 20
Max Error Tol= 0.3
Flow Tol Ratio= 0.001
Split Flow NTrial= 30
Split Flow Tol= 0.02
Split Flow Ratio= 0.02
Log Output Level= 0
Friction Slope Method= 1
Unsteady Friction Slope Method= 2
Unsteady Bridges Friction Slope Method= 1
Parabolic Critical Depth
Global Vel Dist=  1 , 1 , 1
Global Log Level= 0
CheckData=True
Encroach Param= -1, 0, 0, 0
BEGIN DESCRIPTION:
Multiple Run
END DESCRIPTION:

--- Elm 75.f01 (steady flow) ---

Flow Title=Multiple
Number of Profiles=7
Profile Names=10-year,25-year,50-year,1pct_min,100-year,1pct_plu,500-year
River Rch & RM= Elm 75,Reach-1,1482
      74      96     114      84     135     186     191
Boundary for River Rch & Prof#=Elm 75,Reach-1,1
Up Type=0
Dn Type=3
Dn Slope=0.005
Boundary for River Rch & Prof#=Elm 75,Reach-1,2
Up Type=0
Dn Type=3
Dn Slope=0.005
Boundary for River Rch & Prof#=Elm 75,Reach-1,3
Up Type=0
Dn Type=3
Dn Slope=0.005
Boundary for River Rch & Prof#=Elm 75,Reach-1,4
Up Type=0
Dn Type=3
Dn Slope=0.005
Boundary for River Rch & Prof#=Elm 75,Reach-1,5
Up Type=0
Dn Type=3
Dn Slope=0.005
Boundary for River Rch & Prof#=Elm 75,Reach-1,6
Up Type=0
Dn Type=3
Dn Slope=0.005
Boundary for River Rch & Prof#=Elm 75,Reach-1,7
Up Type=0
Dn Type=3
Dn Slope=0.005

--- Elm 75.g01 (geometry) ---

Geom Title=Existing Conditions

River Reach=Elm 75,Reach-1
Reach XY= 30
      1526555.00      6763388.00      1526586.88      6763388.07
      1526607.51      6763382.67      1526688.25      6763304.46
      1526706.50      6763291.61      1526799.02      6763285.64
      1526814.63      6763277.10      1526848.94      6763246.14
      1526865.51      6763239.23      1526999.14      6763235.53
      1527045.10      6763199.47      1527055.00      6763195.56
      1527110.89      6763235.45      1527203.40      6763241.85
      1527248.94      6763279.86      1527265.50      6763286.78
      1527539.79      6763288.54      1527561.08      6763296.19
      1527602.83      6763332.60      1527630.04      6763338.31
      1527657.30      6763332.34      1527695.13      6763299.40
      1527708.41      6763295.85      1527725.03      6763307.38
      1527798.33      6763378.77      1527811.67      6763378.63
      1527845.00      6763349.85      1527858.33      6763345.52
      1527871.78      6763353.69      1527905.00      6763388.00

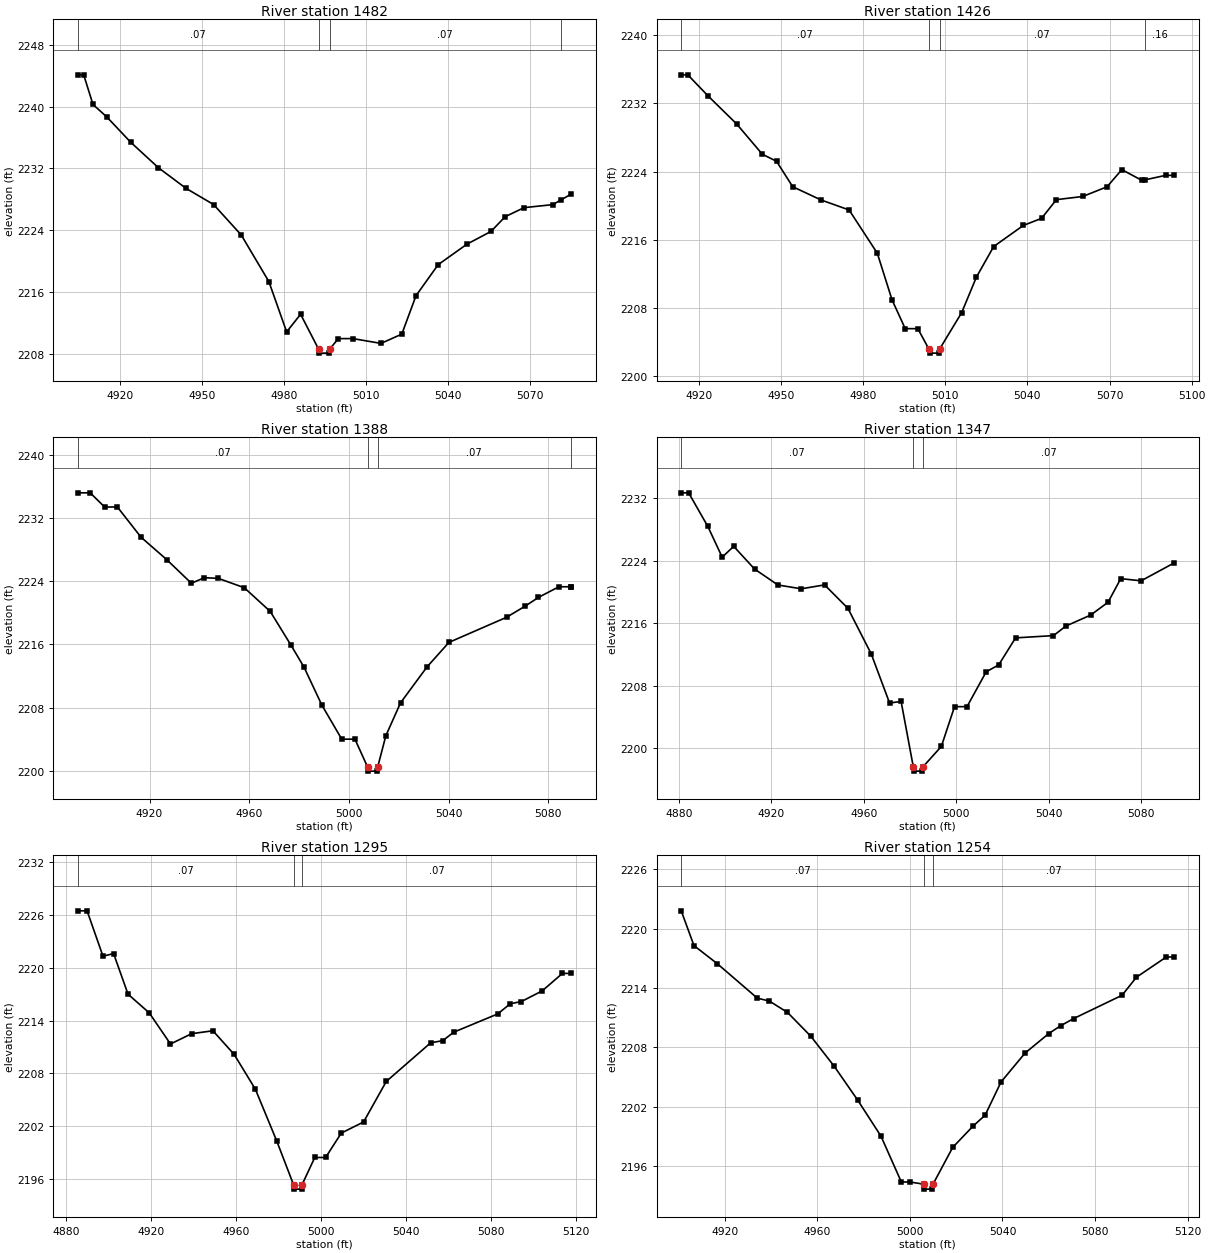
Type RM Length L Ch R = 1,1482,56,56,56
BEGIN DESCRIPTION:
Elm 75 4314
END DESCRIPTION:
XS GIS Cut Line= 3
      1526620.97      6763477.12      1526607.51      6763382.67
      1526582.38      6763301.57
#Sta/Elev= 29
  4904.6 2244.10  4906.7 2244.10  4910.1 2240.26  4915.2 2238.63  4923.9 2235.37
  4934.0 2232.08  4944.1 2229.41  4954.2 2227.31  4964.3 2223.37  4974.4 2217.34
  4980.9 2210.83  4986.0 2213.11  4992.6 2208.58  4992.9 2208.08  4996.4 2208.08
  4996.6 2208.58  4999.8 2209.96  5005.1 2209.96  5015.4 2209.34  5023.0 2210.54
  5028.2 2215.52  5036.3 2219.53  5046.8 2222.18  5055.6 2223.83  5060.8 2225.74
  5067.7 2226.91  5078.2 2227.30  5081.1 2227.89  5084.9 2228.66
#Mann=4,-1,0
  4904.6    0.07       0  4992.6    0.07       0  4996.6    0.07       0
  5081.1    0.16       0
Bank Sta=4992.6,4996.6
Exp/Cntr=0.3,0.1

Type RM Length L Ch R = 1,1426,38,38,38
BEGIN DESCRIPTION:
Elm 75 4315
END DESCRIPTION:
XS GIS Cut Line= 3
      1526667.84      6763427.63      1526647.88      6763343.57
      1526611.85      6763257.07
#Sta/Elev= 30
  4913.6 2235.36  4916.0 2235.36  4923.5 2232.85  4933.8 2229.61  4943.2 2226.05
  4948.4 2225.22  4954.3 2222.24  4964.6 2220.69  4974.9 2219.51  4985.2 2214.44
  4990.6 2208.95  4995.4 2205.59  5000.0 2205.59  5004.0 2203.22  5004.3 2202.72
  5007.8 2202.72  5008.0 2203.22  5016.0 2207.46  5021.4 2211.64  5027.7 2215.22
  5038.5 2217.69  5045.2 2218.53  5050.6 2220.72  5060.2 2221.09  5069.1 2222.23
  5074.5 2224.24  5081.9 2222.97  5082.8 2223.03  5090.5 2223.57  5093.7 2223.57
#Mann=4,-1,0
  4913.6    0.07       0  5004.0    0.07       0  5008.0    0.07       0
  5082.8    0.16       0
Bank Sta=5004,5008
Exp/Cntr=0.3,0.1

Type RM Length L Ch R = 1,1388,41,41,41
BEGIN DESCRIPTION:
Elm 75 4318
END DESCRIPTION:
XS GIS Cut Line= 3
      1526703.00      6763422.42      1526674.86      6763317.43
      1526644.42      6763233.69
#Sta/Elev= 30
  4891.3 2235.21  4896.2 2235.21  4902.0 2233.41  4907.1 2233.42  4916.6 2229.59
  4926.9 2226.75  4936.8 2223.75  4942.0 2224.46  4947.6 2224.37  4958.0 2223.19
  4968.4 2220.19  4976.8 2215.88  4982.0 2213.11  4989.1 2208.33  4997.1 2204.00
  5002.4 2204.00  5007.5 2200.45  5007.7 2199.95  5011.2 2199.95  5011.5 2200.45
  5014.8 2204.44  5020.7 2208.61  5031.3 2213.15  5040.1 2216.26  5063.2 2219.44
  5070.7 2220.86  5076.0 2221.96  5084.2 2223.31  5088.9 2223.31  5089.1 2223.31
#Mann=4,-1,0
  4891.3    0.07       0  5007.5    0.07       0  5011.5    0.07       0
  5088.9    0.16       0
Bank Sta=5007.5,5011.5
Exp/Cntr=0.3,0.1

Type RM Length L Ch R = 1,1347,52,52,52
BEGIN DESCRIPTION:
Elm 75 4316
END DESCRIPTION:
XS GIS Cut Line= 3
      1526722.54      6763409.42      1526706.50      6763291.61
      1526669.58      6763204.73
#Sta/Elev= 30
  4881.1 2232.71  4884.3 2232.71  4892.6 2228.41  4898.8 2224.48  4903.8 2225.86
  4912.8 2222.96  4922.9 2220.92  4933.0 2220.43  4943.1 2220.93  4953.2 2217.93
  4963.3 2212.08  4971.2 2205.82  4976.2 2206.01  4981.5 2197.60  4981.7 2197.10
  4985.2 2197.10  4985.5 2197.60  4993.6 2200.26  4999.3 2205.35  5004.7 2205.35
  5013.0 2209.81  5018.4 2210.69  5025.7 2214.15  5042.1 2214.44  5047.5 2215.67
  5058.2 2217.07  5065.7 2218.71  5071.2 2221.73  5080.0 2221.45  5094.4 2223.76
#Mann=3,-1,0
  4881.1    0.07       0  4981.5    0.07       0  4985.5    0.07       0
Bank Sta=4981.5,4985.5
Exp/Cntr=0.3,0.1

Type RM Length L Ch R = 1,1295,41,41,41
BEGIN DESCRIPTION:
Elm 75 4317
END DESCRIPTION:
XS GIS Cut Line= 3
      1526760.30      6763401.60      1526758.00      6763287.02
      1526721.25      6763175.10
#Sta/Elev= 30
  4885.4 2226.45  4889.7 2226.45  4897.2 2221.30  4902.2 2221.60  4909.0 2216.99
  4919.0 2214.87  4929.0 2211.34  4939.0 2212.51  4949.0 2212.84  4959.0 2210.16
  4969.0 2206.21  4979.0 2200.38  4987.0 2195.37  4987.3 2194.87  4990.8 2194.87
  4991.0 2195.37  4997.0 2198.46  5002.1 2198.46  5009.5 2201.23  5020.0 2202.49
  5030.7 2207.09  5051.6 2211.47  5057.3 2211.72  5062.5 2212.68  5083.2 2214.75
  5089.1 2215.90  5094.4 2216.16  5104.2 2217.37  5113.7 2219.35  5117.8 2219.35
#Mann=3,-1,0
  4885.4    0.07       0  4987.0    0.07       0  4991.0    0.07       0
Bank Sta=4987,4991
Exp/Cntr=0.3,0.1

Type RM Length L Ch R = 1,1254,40,40,40
BEGIN DESCRIPTION:
Elm 75 4313
END DESCRIPTION:
XS GIS Cut Line= 3
      1526785.04      6763383.45      1526799.02      6763285.64
      1526765.51      6763176.37
#Sta/Elev= 28
  4901.2 2221.79  4906.7 2218.28  4916.8 2216.45  4934.1 2212.97  4939.2 2212.69
  4947.1 2211.54  4957.2 2209.13  4967.3 2206.10  4977.4 2202.70  4987.5 2199.05
  4996.3 2194.42  5000.0 2194.42  5006.0 2194.20  5006.2 2193.70  5009.7 2193.70
  5010.0 2194.20  5018.5 2197.91  5027.2 2200.04  5032.5 2201.16  5039.4 2204.52
  5049.8 2207.44  5060.0 2209.40  5065.2 2210.20  5070.8 2210.92  5091.7 2213.27
  5097.9 2215.09  5110.8 2217.13  5114.3 2217.13
#Mann=3,-1,0
  4901.2    0.07       0  5006.0    0.07       0  5010.0    0.07       0
Bank Sta=5006,5010
Exp/Cntr=0.3,0.1

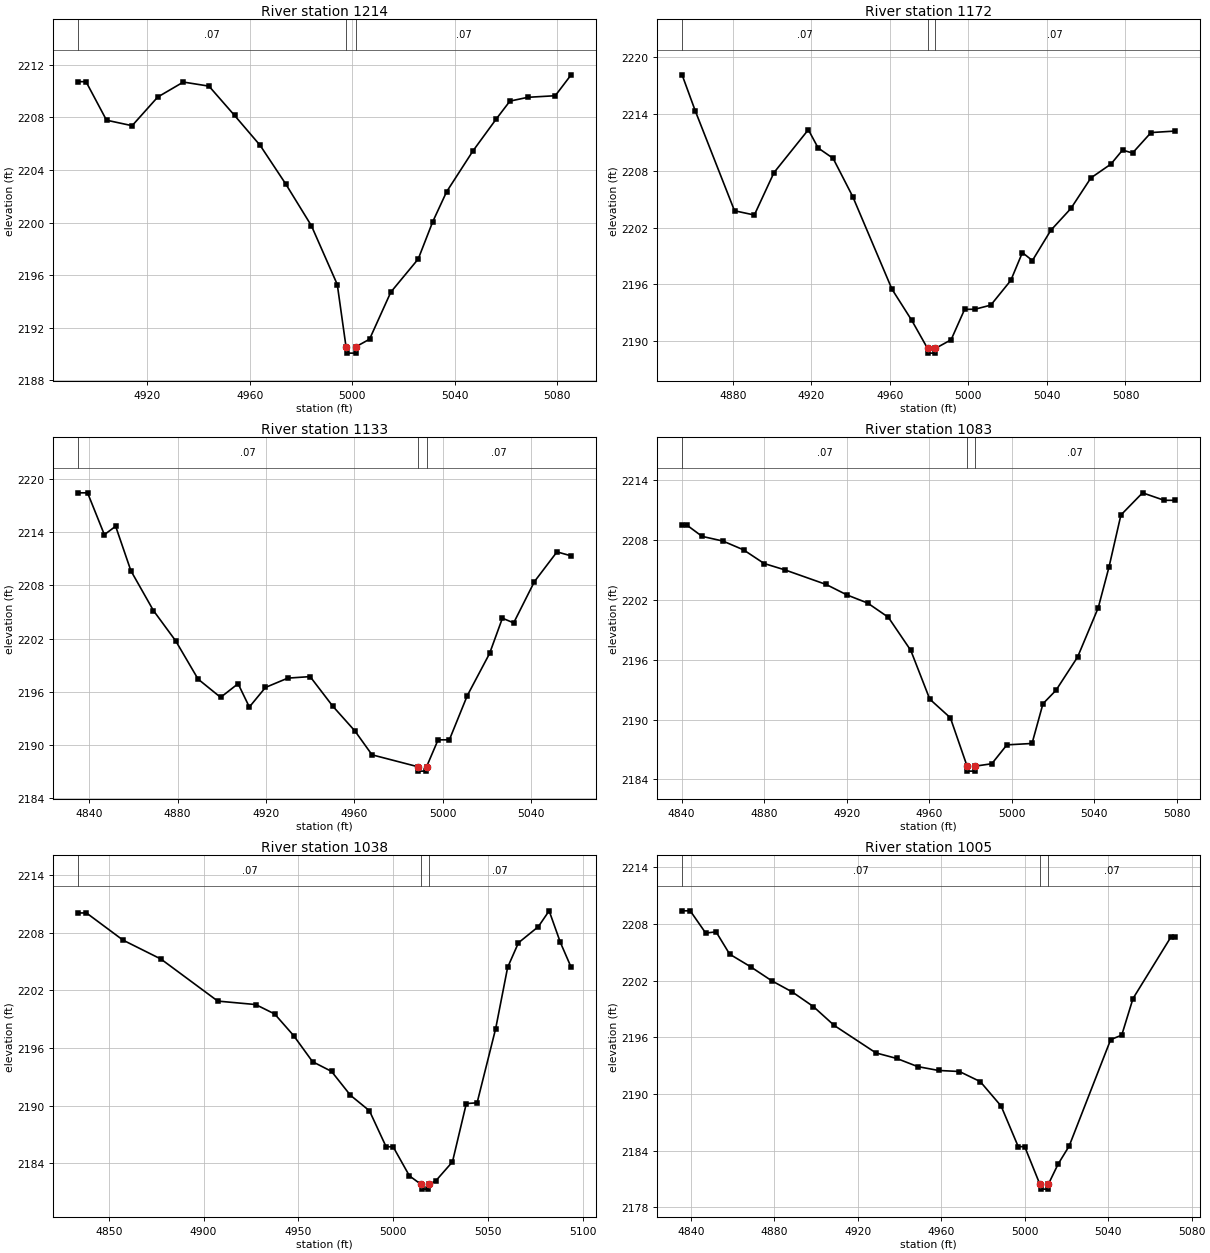
Type RM Length L Ch R = 1,1214,42,42,42
BEGIN DESCRIPTION:
Elm 75 4312
END DESCRIPTION:
XS GIS Cut Line= 3
      1526834.52      6763369.11      1526831.31      6763262.06
      1526800.92      6763182.25
#Sta/Elev= 27
  4892.9 2210.72  4896.0 2210.72  4904.0 2207.79  4914.0 2207.37  4924.0 2209.55
  4934.0 2210.69  4944.0 2210.38  4954.0 2208.15  4964.0 2205.87  4974.0 2202.93
  4984.0 2199.76  4994.1 2195.29  4997.5 2190.57  4997.8 2190.07  5001.3 2190.07
  5001.5 2190.57  5006.7 2191.13  5015.0 2194.71  5025.7 2197.23  5031.4 2200.08
  5036.8 2202.35  5047.1 2205.46  5056.2 2207.89  5061.5 2209.24  5068.5 2209.53
  5079.2 2209.65  5085.4 2211.24
#Mann=3,-1,0
  4892.9    0.07       0  4997.5    0.07       0  5001.5    0.07       0
Bank Sta=4997.5,5001.5
Exp/Cntr=0.3,0.1

Type RM Length L Ch R = 1,1172,39,39,39
BEGIN DESCRIPTION:
Elm 75 4311
END DESCRIPTION:
XS GIS Cut Line= 3
      1526855.36      6763384.68      1526865.51      6763239.23
      1526844.93      6763135.96
#Sta/Elev= 30
  4854.2 2218.14  4860.9 2214.34  4880.9 2203.78  4891.0 2203.33  4901.0 2207.81
  4918.5 2212.34  4923.5 2210.41  4931.1 2209.32  4941.1 2205.28  4961.1 2195.49
  4971.2 2192.19  4979.2 2189.24  4979.4 2188.74  4982.9 2188.74  4983.2 2189.24
  4991.2 2190.15  4998.1 2193.37  5003.2 2193.37  5011.4 2193.81  5021.6 2196.42
  5027.5 2199.36  5032.6 2198.52  5042.0 2201.72  5052.2 2204.02  5062.4 2207.25
  5072.6 2208.71  5078.5 2210.19  5083.6 2209.88  5093.0 2212.04  5105.3 2212.20
#Mann=3,-1,0
  4854.2    0.07       0  4979.2    0.07       0  4983.2    0.07       0
Bank Sta=4979.2,4983.2
Exp/Cntr=0.3,0.1

Type RM Length L Ch R = 1,1133,50,50,50
BEGIN DESCRIPTION:
Elm 75 4310
END DESCRIPTION:
XS GIS Cut Line= 3
      1526877.50      6763401.59      1526904.89      6763238.88
      1526894.67      6763181.68
#Sta/Elev= 30
  4835.0 2218.45  4839.3 2218.45  4846.9 2213.73  4852.0 2214.68  4858.9 2209.66
  4869.1 2205.17  4879.2 2201.74  4889.3 2197.44  4899.5 2195.38  4907.4 2196.92
  4912.5 2194.29  4919.8 2196.50  4929.9 2197.55  4940.0 2197.72  4950.2 2194.40
  4960.3 2191.58  4968.0 2188.90  4988.7 2187.56  4989.0 2187.06  4992.5 2187.06
  4992.7 2187.56  4997.9 2190.59  5003.0 2190.59  5011.1 2195.57  5021.2 2200.33
  5027.0 2204.31  5032.1 2203.78  5041.5 2208.44  5051.7 2211.79  5058.1 2211.34
#Mann=3,-1,0
  4835.0    0.07       0  4988.7    0.07       0  4992.7    0.07       0
Bank Sta=4988.7,4992.7
Exp/Cntr=0.3,0.1

Type RM Length L Ch R = 1,1083,45,45,45
BEGIN DESCRIPTION:
Elm 75 4309
END DESCRIPTION:
XS GIS Cut Line= 3
      1526941.29      6763397.70      1526954.33      6763238.44
      1526929.99      6763162.97
#Sta/Elev= 30
  4840.2 2209.47  4842.5 2209.47  4849.9 2208.34  4860.0 2207.87  4870.0 2206.99
  4880.0 2205.62  4890.1 2204.98  4910.1 2203.52  4920.2 2202.47  4930.2 2201.66
  4940.2 2200.24  4951.1 2196.92  4960.3 2192.04  4970.3 2190.17  4978.4 2185.33
  4978.6 2184.83  4982.1 2184.83  4982.4 2185.33  4990.4 2185.57  4997.7 2187.46
  5009.9 2187.60  5015.2 2191.58  5021.5 2192.92  5032.0 2196.26  5042.0 2201.19
  5047.2 2205.25  5053.0 2210.48  5063.5 2212.70  5074.0 2211.95  5079.3 2211.95
#Mann=3,-1,0
  4840.2    0.07       0  4978.4    0.07       0  4982.4    0.07       0
Bank Sta=4978.4,4982.4
Exp/Cntr=0.3,0.1

Type RM Length L Ch R = 1,1038,33,33,33
BEGIN DESCRIPTION:
Elm 75 1038.388
END DESCRIPTION:
XS GIS Cut Line= 3
      1526994.68      6763401.67      1526999.14      6763235.53
      1526954.35      6763153.00
#Sta/Elev= 30
  4833.8 2210.07  4838.2 2210.07  4857.5 2207.24  4877.5 2205.27  4907.5 2200.89
  4927.5 2200.53  4937.5 2199.55  4947.5 2197.30  4957.5 2194.58  4967.5 2193.57
  4977.5 2191.08  4987.5 2189.47  4996.3 2185.72  5000.0 2185.72  5008.6 2182.69
  5014.7 2181.81  5015.0 2181.31  5018.5 2181.31  5018.7 2181.81  5022.4 2182.15
  5031.3 2184.15  5038.6 2190.22  5044.3 2190.30  5054.1 2198.03  5060.4 2204.40
  5066.1 2206.96  5076.6 2208.64  5082.3 2210.29  5088.2 2207.01  5093.9 2204.41
#Mann=3,-1,0
  4833.8    0.07       0  5014.7    0.07       0  5018.7    0.07       0
Bank Sta=5014.7,5018.7
Exp/Cntr=0.3,0.1

Type RM Length L Ch R = 1,1005,42,42,42
BEGIN DESCRIPTION:
Elm 75 1005.47
END DESCRIPTION:
XS GIS Cut Line= 3
      1527019.42      6763380.82      1527025.93      6763216.74
      1527001.19      6763149.03
#Sta/Elev= 30
  4835.8 2209.39  4839.7 2209.39  4847.1 2207.04  4852.1 2207.16  4858.6 2204.80
  4868.6 2203.47  4878.7 2201.99  4888.7 2200.78  4898.7 2199.25  4908.7 2197.25
  4928.7 2194.34  4938.7 2193.75  4948.7 2192.89  4958.7 2192.48  4968.7 2192.37
  4978.7 2191.30  4988.7 2188.71  4996.9 2184.41  5000.0 2184.41  5007.3 2180.41
  5007.6 2179.91  5011.1 2179.91  5011.3 2180.41  5016.0 2182.56  5021.3 2184.47
  5041.2 2195.75  5046.5 2196.22  5051.9 2200.10  5070.0 2206.59  5072.1 2206.59
#Mann=3,-1,0
  4835.8    0.07       0  5007.3    0.07       0  5011.3    0.07       0
Bank Sta=5007.3,5011.3
Exp/Cntr=0.3,0.1

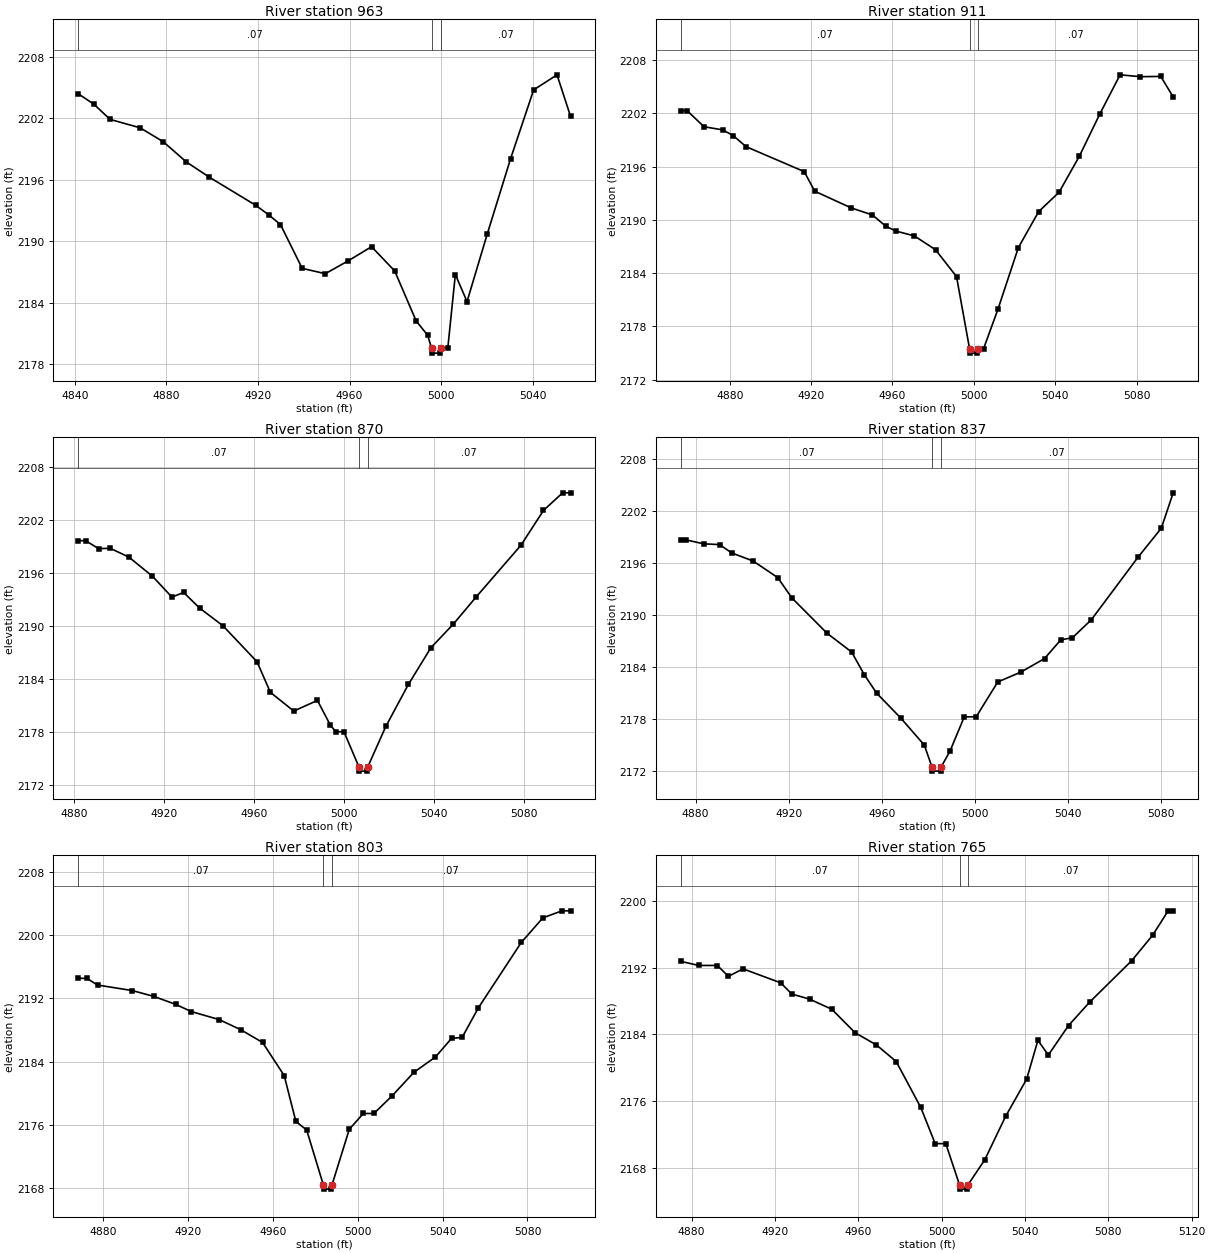
Type RM Length L Ch R = 1,963,52,52,52
BEGIN DESCRIPTION:
Elm 75 962.59
END DESCRIPTION:
XS GIS Cut Line= 3
      1527037.64      6763354.79      1527061.08      6763197.21
      1527052.12      6763142.15
#Sta/Elev= 29
  4841.4 2204.43  4848.3 2203.40  4855.4 2201.91  4868.5 2201.09  4878.6 2199.73
  4888.7 2197.75  4898.8 2196.25  4919.0 2193.51  4924.7 2192.57  4929.8 2191.63
  4939.3 2187.34  4949.4 2186.82  4959.5 2188.09  4969.6 2189.46  4979.7 2187.09
  4989.1 2182.19  4994.1 2180.80  4995.8 2179.55  4996.0 2179.05  4999.5 2179.05
  4999.8 2179.55  5002.9 2179.55  5006.2 2186.74  5011.3 2184.09  5020.2 2190.75
  5030.3 2198.05  5040.4 2204.80  5050.6 2206.27  5056.5 2202.22
#Mann=3,-1,0
  4841.4    0.07       0  4995.8    0.07       0  4999.8    0.07       0
Bank Sta=4995.8,4999.8
Exp/Cntr=0.3,0.1

Type RM Length L Ch R = 1,911,41,41,41
BEGIN DESCRIPTION:
Elm 75 911.27
END DESCRIPTION:
XS GIS Cut Line= 3
      1527063.69      6763369.07      1527101.45      6763227.15
      1527100.16      6763131.91
#Sta/Elev= 30
  4855.9 2202.32  4859.0 2202.32  4867.4 2200.50  4876.5 2200.15  4881.7 2199.51
  4888.0 2198.26  4916.6 2195.45  4921.8 2193.24  4939.8 2191.35  4950.1 2190.57
  4956.8 2189.28  4961.9 2188.74  4970.8 2188.20  4981.2 2186.64  4991.5 2183.62
  4997.9 2175.50  4998.2 2175.00  5001.7 2175.00  5001.9 2175.50  5004.8 2175.50
  5011.9 2179.97  5021.9 2186.89  5031.9 2190.95  5041.9 2193.12  5051.9 2197.19
  5061.9 2201.92  5071.9 2206.35  5081.9 2206.14  5091.9 2206.17  5098.0 2203.86
#Mann=3,-1,0
  4855.9    0.07       0  4997.9    0.07       0  5001.9    0.07       0
Bank Sta=4997.9,5001.9
Exp/Cntr=0.3,0.1

Type RM Length L Ch R = 1,870,33,33,33
BEGIN DESCRIPTION:
Elm 75 870.02
END DESCRIPTION:
XS GIS Cut Line= 3
      1527106.66      6763349.54      1527140.51      6763240.18
      1527140.51      6763135.96
#Sta/Elev= 30
  4881.9 2199.66  4885.3 2199.66  4891.0 2198.76  4896.2 2198.80  4904.5 2197.80
  4914.9 2195.65  4923.6 2193.28  4928.8 2193.81  4935.9 2192.04  4946.3 2190.03
  4961.4 2185.97  4967.3 2182.52  4977.7 2180.40  4988.2 2181.60  4994.0 2178.79
  4996.4 2178.06  5000.0 2178.06  5006.6 2174.11  5006.8 2173.61  5010.3 2173.61
  5010.6 2174.11  5018.6 2178.67  5028.6 2183.41  5038.6 2187.56  5048.6 2190.24
  5058.6 2193.27  5078.6 2199.15  5088.6 2203.08  5097.1 2205.07  5100.6 2205.07
#Mann=3,-1,0
  4881.9    0.07       0  5006.6    0.07       0  5010.6    0.07       0
Bank Sta=5006.6,5010.6
Exp/Cntr=0.3,0.1

Type RM Length L Ch R = 1,837,34,34,34
BEGIN DESCRIPTION:
Elm 75 836.52
END DESCRIPTION:
XS GIS Cut Line= 3
      1527134.00      6763357.37      1527174.36      6763241.48
      1527165.25      6763152.97
#Sta/Elev= 30
  4873.6 2198.66  4875.9 2198.66  4883.5 2198.21  4890.3 2198.12  4895.6 2197.15
  4904.7 2196.23  4915.3 2194.32  4921.4 2191.97  4936.5 2187.90  4947.1 2185.73
  4952.5 2183.13  4957.8 2181.00  4968.2 2178.12  4978.3 2175.01  4981.6 2172.50
  4981.8 2172.00  4985.3 2172.00  4985.6 2172.50  4989.4 2174.33  4995.5 2178.26
  5000.6 2178.26  5009.9 2182.28  5019.9 2183.43  5030.0 2184.98  5037.0 2187.14
  5042.0 2187.38  5050.1 2189.45  5070.2 2196.67  5080.2 2200.01  5085.3 2204.09
#Mann=3,-1,0
  4873.6    0.07       0  4981.6    0.07       0  4985.6    0.07       0
Bank Sta=4981.6,4985.6
Exp/Cntr=0.3,0.1

Type RM Length L Ch R = 1,803,38,38,38
BEGIN DESCRIPTION:
Elm 75 803.27
END DESCRIPTION:
XS GIS Cut Line= 3
      1527178.26      6763373.02      1527206.92      6763240.18
      1527191.30      6763145.15
#Sta/Elev= 30
  4868.1 2194.53  4872.2 2194.53  4877.3 2193.68  4893.7 2192.98  4903.9 2192.24
  4914.2 2191.23  4921.5 2190.33  4934.6 2189.32  4944.8 2188.04  4955.1 2186.43
  4965.3 2182.25  4970.8 2176.46  4975.9 2175.37  4983.8 2168.41  4984.0 2167.91
  4987.5 2167.91  4987.8 2168.41  4996.0 2175.47  5002.6 2177.46  5007.6 2177.46
  5016.3 2179.72  5026.5 2182.67  5036.6 2184.59  5044.2 2186.94  5049.2 2187.07
  5056.9 2190.82  5077.1 2199.06  5087.3 2202.17  5096.3 2203.05  5100.3 2203.05
#Mann=3,-1,0
  4868.1    0.07       0  4983.8    0.07       0  4987.8    0.07       0
Bank Sta=4983.8,4987.8
Exp/Cntr=0.3,0.1

Type RM Length L Ch R = 1,765,40,40,40
BEGIN DESCRIPTION:
Elm 75 765.1
END DESCRIPTION:
XS GIS Cut Line= 3
      1527192.59      6763386.02      1527235.56      6763270.12
      1527222.55      6763158.19
#Sta/Elev= 30
  4874.8 2192.75  4883.4 2192.26  4892.4 2192.25  4897.7 2190.95  4904.7 2191.85
  4922.8 2190.17  4928.1 2188.83  4936.7 2188.21  4947.3 2187.00  4958.5 2184.18
  4968.7 2182.72  4978.2 2180.73  4990.0 2175.22  4996.9 2170.88  5002.0 2170.88
  5008.6 2165.92  5008.9 2165.42  5012.4 2165.42  5012.6 2165.92  5020.7 2168.94
  5030.7 2174.15  5040.8 2178.62  5046.2 2183.27  5051.2 2181.51  5060.9 2185.05
  5071.0 2187.85  5091.2 2192.83  5101.2 2195.87  5108.7 2198.81  5111.1 2198.81
#Mann=3,-1,0
  4874.8    0.07       0  5008.6    0.07       0  5012.6    0.07       0
Bank Sta=5008.6,5012.6
Exp/Cntr=0.3,0.1

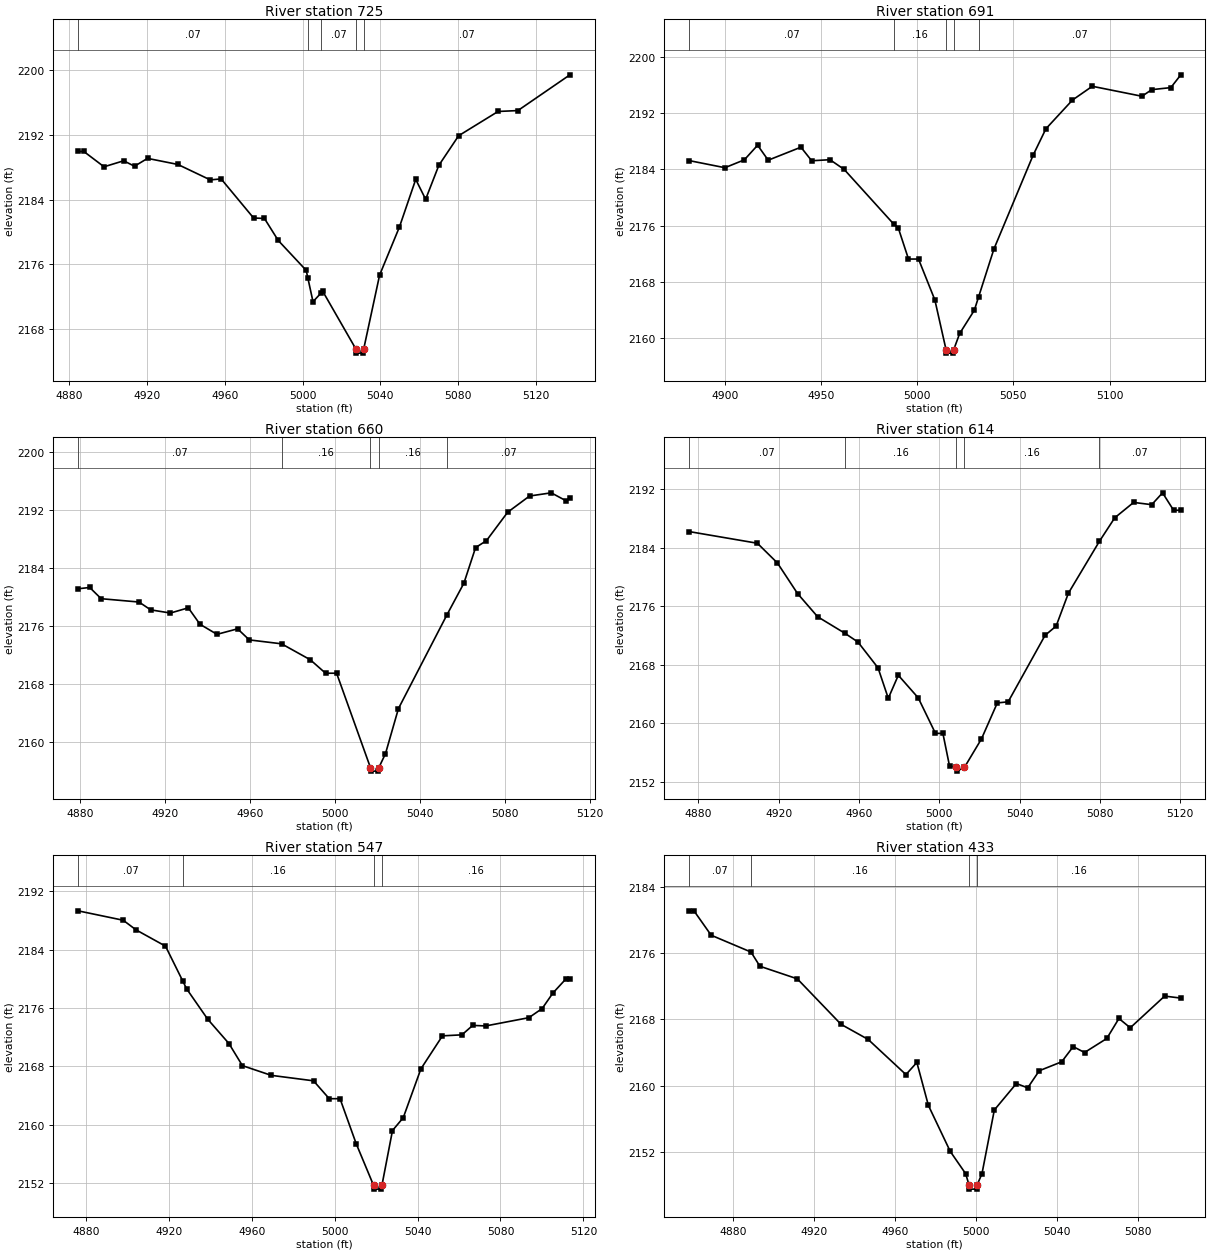
Type RM Length L Ch R = 1,725,34,34,34
BEGIN DESCRIPTION:
Elm 75 725.46
END DESCRIPTION:
XS GIS Cut Line= 3
      1527217.32      6763389.95      1527270.72      6763284.45
      1527246.22      6763151.63
#Sta/Elev= 30
  4884.4 2189.94  4887.4 2189.94  4897.8 2188.05  4907.9 2188.79  4913.5 2188.12
  4920.2 2189.09  4935.8 2188.34  4952.5 2186.43  4958.1 2186.55  4974.8 2181.72
  4980.4 2181.66  4987.5 2178.94  5001.9 2175.24  5002.7 2174.36  5005.4 2171.37
  5009.7 2172.48  5010.4 2172.66  5027.5 2165.51  5027.8 2165.01  5031.3 2165.01
  5031.5 2165.51  5039.7 2174.66  5049.9 2180.60  5058.3 2186.49  5063.4 2184.03
  5070.2 2188.23  5080.4 2191.89  5100.7 2194.89  5110.9 2195.00  5137.7 2199.42
#Mann=5,-1,0
  4884.4    0.07       0  5002.7    0.16       0  5009.7    0.07       0
  5027.5    0.07       0  5031.5    0.07       0
Bank Sta=5027.5,5031.5
Exp/Cntr=0.3,0.1

Type RM Length L Ch R = 1,691,31,31,31
BEGIN DESCRIPTION:
Elm 75 690.96
END DESCRIPTION:
XS GIS Cut Line= 3
      1527253.78      6763393.85      1527304.57      6763289.65
      1527275.93      6763152.94
#Sta/Elev= 30
  4881.4 2185.25  4900.1 2184.23  4910.2 2185.35  4917.1 2187.43  4922.6 2185.30
  4939.6 2187.15  4945.2 2185.22  4954.7 2185.37  4962.1 2183.98  4987.9 2176.18
  4990.2 2175.65  4995.5 2171.23  5000.7 2171.23  5009.2 2165.41  5015.0 2158.34
  5015.2 2157.84  5018.7 2157.84  5019.0 2158.34  5022.1 2160.64  5029.7 2163.94
  5031.9 2165.82  5039.9 2172.67  5060.3 2186.04  5066.9 2189.77  5080.7 2193.86
  5091.0 2195.82  5116.8 2194.40  5121.9 2195.34  5131.8 2195.63  5137.0 2197.45
#Mann=5,-1,0
  4881.4    0.07       0  4987.9    0.16       0  5015.0    0.07       0
  5019.0    0.16       0  5031.9    0.07       0
Bank Sta=5015,5019
Exp/Cntr=0.3,0.1

Type RM Length L Ch R = 1,660,46,46,46
BEGIN DESCRIPTION:
Elm 75 659.73
END DESCRIPTION:
XS GIS Cut Line= 3
      1527287.65      6763397.71      1527335.82      6763289.65
      1527309.90      6763179.47
#Sta/Elev= 30
  4879.2 2181.18  4884.7 2181.36  4890.1 2179.81  4907.9 2179.35  4913.4 2178.27
  4922.7 2177.83  4931.1 2178.55  4936.6 2176.28  4944.6 2174.89  4954.3 2175.65
  4959.8 2174.12  4975.0 2173.58  4988.5 2171.38  4995.7 2169.52  5000.9 2169.52
  5016.8 2156.50  5017.0 2156.00  5020.5 2156.00  5020.8 2156.50  5023.9 2158.41
  5030.0 2164.64  5052.8 2177.57  5060.8 2181.95  5066.3 2186.87  5071.4 2187.82
  5081.4 2191.75  5091.7 2193.99  5101.9 2194.43  5108.7 2193.36  5110.7 2193.65
#Mann=5,-1,0
  4879.2    0.07       0  4975.0    0.16       0  5016.8    0.07       0
  5020.8    0.16       0  5052.8    0.07       0
Bank Sta=5016.8,5020.8
Exp/Cntr=0.3,0.1

Type RM Length L Ch R = 1,614,67,67,67
BEGIN DESCRIPTION:
Elm 75 613.68
END DESCRIPTION:
XS GIS Cut Line= 3
      1527374.88      6763412.06      1527381.40      6763285.75
      1527335.81      6763176.34
#Sta/Elev= 30
  4875.3 2186.21  4909.4 2184.61  4919.4 2181.91  4929.4 2177.74  4939.4 2174.57
  4953.1 2172.29  4959.5 2171.11  4969.5 2167.58  4974.6 2163.42  4979.6 2166.57
  4989.5 2163.49  4998.1 2158.63  5001.8 2158.63  5005.1 2154.17  5008.5 2153.97
  5008.7 2153.47  5012.5 2153.97  5021.0 2157.87  5028.9 2162.79  5034.3 2162.94
  5052.7 2172.03  5058.2 2173.29  5064.3 2177.78  5079.7 2184.85  5087.4 2188.09
  5096.8 2190.19  5105.8 2189.88  5111.2 2191.50  5116.7 2189.12  5120.3 2189.12
#Mann=5,-1,0
  4875.3    0.07       0  4953.1    0.16       0  5008.5    0.07       0
  5012.5    0.16       0  5079.7    0.07       0
Bank Sta=5008.5,5012.5
Exp/Cntr=0.3,0.1

Type RM Length L Ch R = 1,547,114,114,114
BEGIN DESCRIPTION:
Elm 75 546.616
END DESCRIPTION:
XS GIS Cut Line= 3
      1527424.37      6763409.41      1527448.36      6763287.95
      1527416.56      6763179.00
#Sta/Elev= 30
  4876.2 2189.32  4898.0 2188.03  4904.2 2186.71  4918.4 2184.48  4926.7 2179.72
  4928.6 2178.63  4938.8 2174.46  4949.0 2171.14  4955.5 2168.11  4969.4 2166.78
  4989.8 2166.03  4997.4 2163.58  5002.6 2163.58  5010.4 2157.41  5018.8 2151.69
  5019.0 2151.19  5022.5 2151.19  5022.8 2151.69  5027.9 2159.22  5033.1 2160.98
  5041.6 2167.66  5052.0 2172.19  5061.4 2172.33  5066.6 2173.62  5072.9 2173.55
  5093.7 2174.68  5100.1 2175.93  5105.3 2178.06  5111.4 2179.94  5113.5 2179.94
#Mann=4,-1,0
  4876.2    0.07       0  4926.7    0.16       0  5018.8    0.07       0
  5022.8    0.16       0
Bank Sta=5018.8,5022.8
Exp/Cntr=0.3,0.1

Type RM Length L Ch R = 1,433,97,97,97
BEGIN DESCRIPTION:
Elm 75 4295
END DESCRIPTION:
XS GIS Cut Line= 3
      1527507.70      6763427.67      1527561.08      6763296.19
      1527516.83      6763205.06
#Sta/Elev= 30
  4858.1 2181.07  4860.6 2181.07  4869.1 2178.13  4888.8 2176.10  4893.2 2174.39
  4911.7 2172.87  4933.3 2167.39  4946.7 2165.57  4965.4 2161.33  4970.8 2162.79
  4976.5 2157.61  4987.3 2152.07  4994.9 2149.39  4996.6 2148.02  4996.8 2147.52
  5000.3 2147.52  5000.6 2148.02  5003.0 2149.39  5009.1 2157.06  5020.0 2160.25
  5025.6 2159.73  5031.3 2161.79  5042.4 2162.87  5048.1 2164.70  5053.7 2163.99
  5064.7 2165.68  5070.7 2168.09  5076.3 2166.97  5093.3 2170.79  5101.3 2170.55
#Mann=4,-1,0
  4858.1    0.07       0  4888.8    0.16       0  4996.6    0.07       0
  5000.6    0.16       0
Bank Sta=4996.6,5000.6
Exp/Cntr=0.3,0.1

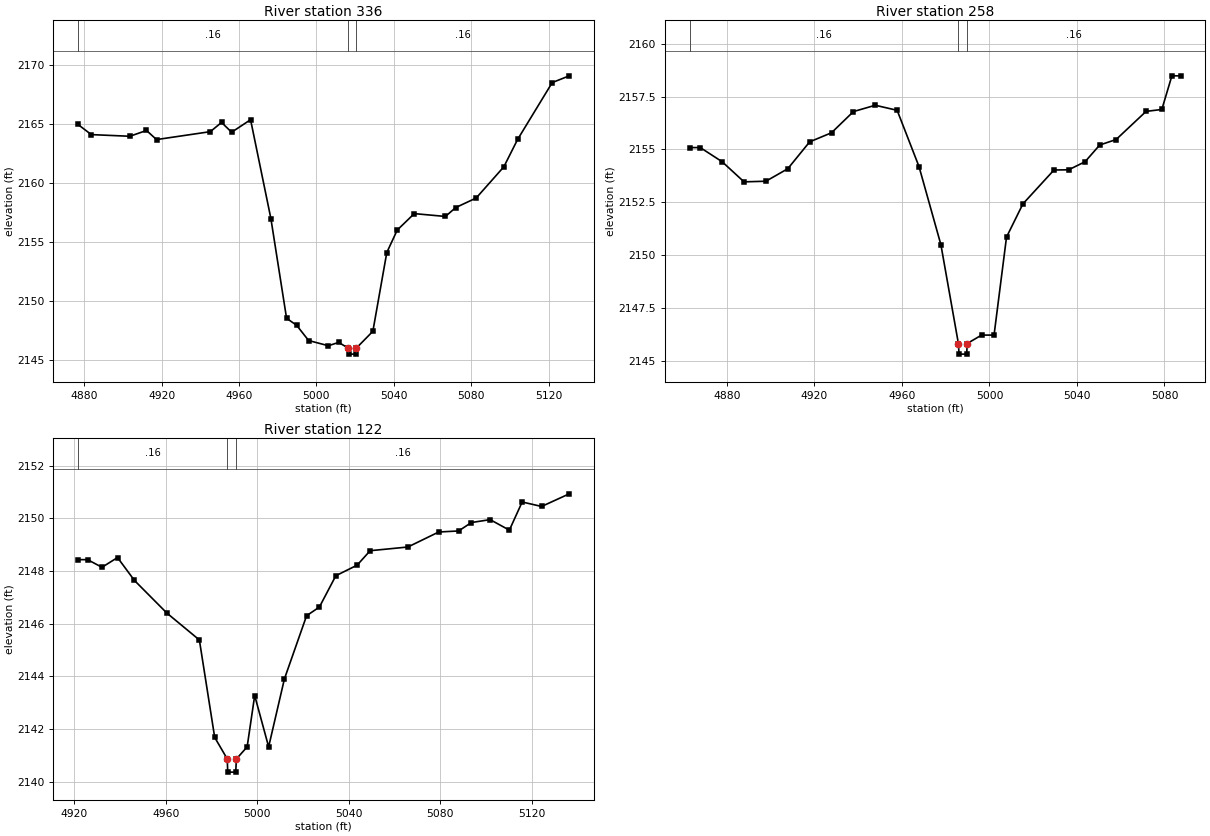
Type RM Length L Ch R = 1,336,78,78,78
BEGIN DESCRIPTION:
Elm 75 4294
END DESCRIPTION:
XS GIS Cut Line= 3
      1527609.25      6763453.74      1527643.43      6763335.38
      1527597.54      6763213.00
#Sta/Elev= 30
  4876.8 2164.95  4883.7 2164.09  4903.6 2163.95  4912.2 2164.44  4917.4 2163.67
  4945.2 2164.34  4951.0 2165.12  4956.2 2164.29  4966.0 2165.35  4976.5 2156.99
  4984.6 2148.56  4989.8 2147.97  4996.0 2146.68  5006.2 2146.24  5011.5 2146.52
  5016.6 2146.03  5016.8 2145.53  5020.3 2145.53  5020.6 2146.03  5029.2 2147.46
  5036.4 2154.12  5041.8 2156.02  5050.6 2157.41  5066.7 2157.17  5072.0 2157.92
  5082.6 2158.73  5096.9 2161.37  5104.0 2163.68  5121.9 2168.49  5130.7 2169.06
#Mann=3,-1,0
  4876.8    0.16       0  5016.6    0.07       0  5020.6    0.16       0
Bank Sta=5016.6,5020.6
Exp/Cntr=0.3,0.1

Type RM Length L Ch R = 1,258,136,136,136
BEGIN DESCRIPTION:
Elm 75 4293
END DESCRIPTION:
XS GIS Cut Line= 3
      1527703.01      6763432.84      1527708.41      6763295.85
      1527643.13      6763237.58
#Sta/Elev= 30
  4862.9 2155.09  4867.8 2155.09  4877.8 2154.42  4887.8 2153.47  4897.8 2153.50
  4907.8 2154.09  4917.8 2155.36  4927.8 2155.79  4937.8 2156.79  4947.8 2157.09
  4957.8 2156.85  4967.8 2154.19  4977.8 2150.50  4985.8 2145.83  4986.1 2145.33
  4989.6 2145.33  4989.8 2145.83  4996.4 2146.23  5002.1 2146.23  5007.8 2150.86
  5015.3 2152.43  5029.5 2154.03  5036.2 2154.04  5043.7 2154.42  5050.4 2155.21
  5057.9 2155.47  5071.6 2156.80  5078.8 2156.89  5083.4 2158.48  5087.5 2158.48
#Mann=3,-1,0
  4862.9    0.16       0  4985.8    0.07       0  4989.8    0.16       0
Bank Sta=4985.8,4989.8
Exp/Cntr=0.3,0.1

Type RM Length L Ch R = 1,122,0,0,0
BEGIN DESCRIPTION:
Elm 75 4292
END DESCRIPTION:
XS GIS Cut Line= 3
      1527753.82      6763431.55      1527811.67      6763378.63
      1527749.30      6763257.21
#Sta/Elev= 30
  4921.6 2148.43  4925.8 2148.43  4932.1 2148.14  4938.9 2148.51  4946.3 2147.64
  4960.5 2146.40  4974.7 2145.38  4981.4 2141.68  4986.9 2140.86  4987.1 2140.36
  4990.6 2140.36  4990.9 2140.86  4995.6 2141.32  4998.9 2143.27  5005.0 2141.32
  5011.9 2143.90  5021.6 2146.30  5027.2 2146.63  5034.4 2147.82  5043.7 2148.22
  5049.4 2148.77  5065.9 2148.91  5079.4 2149.48  5088.1 2149.52  5093.7 2149.84
  5101.9 2149.95  5110.3 2149.55  5115.9 2150.62  5124.4 2150.45  5136.5 2150.93
#Mann=3,-1,0
  4921.6    0.16       0  4986.9    0.07       0  4990.9    0.16       0
Bank Sta=4986.9,4990.9
Exp/Cntr=0.3,0.1

Chan Stop Cuts=-1