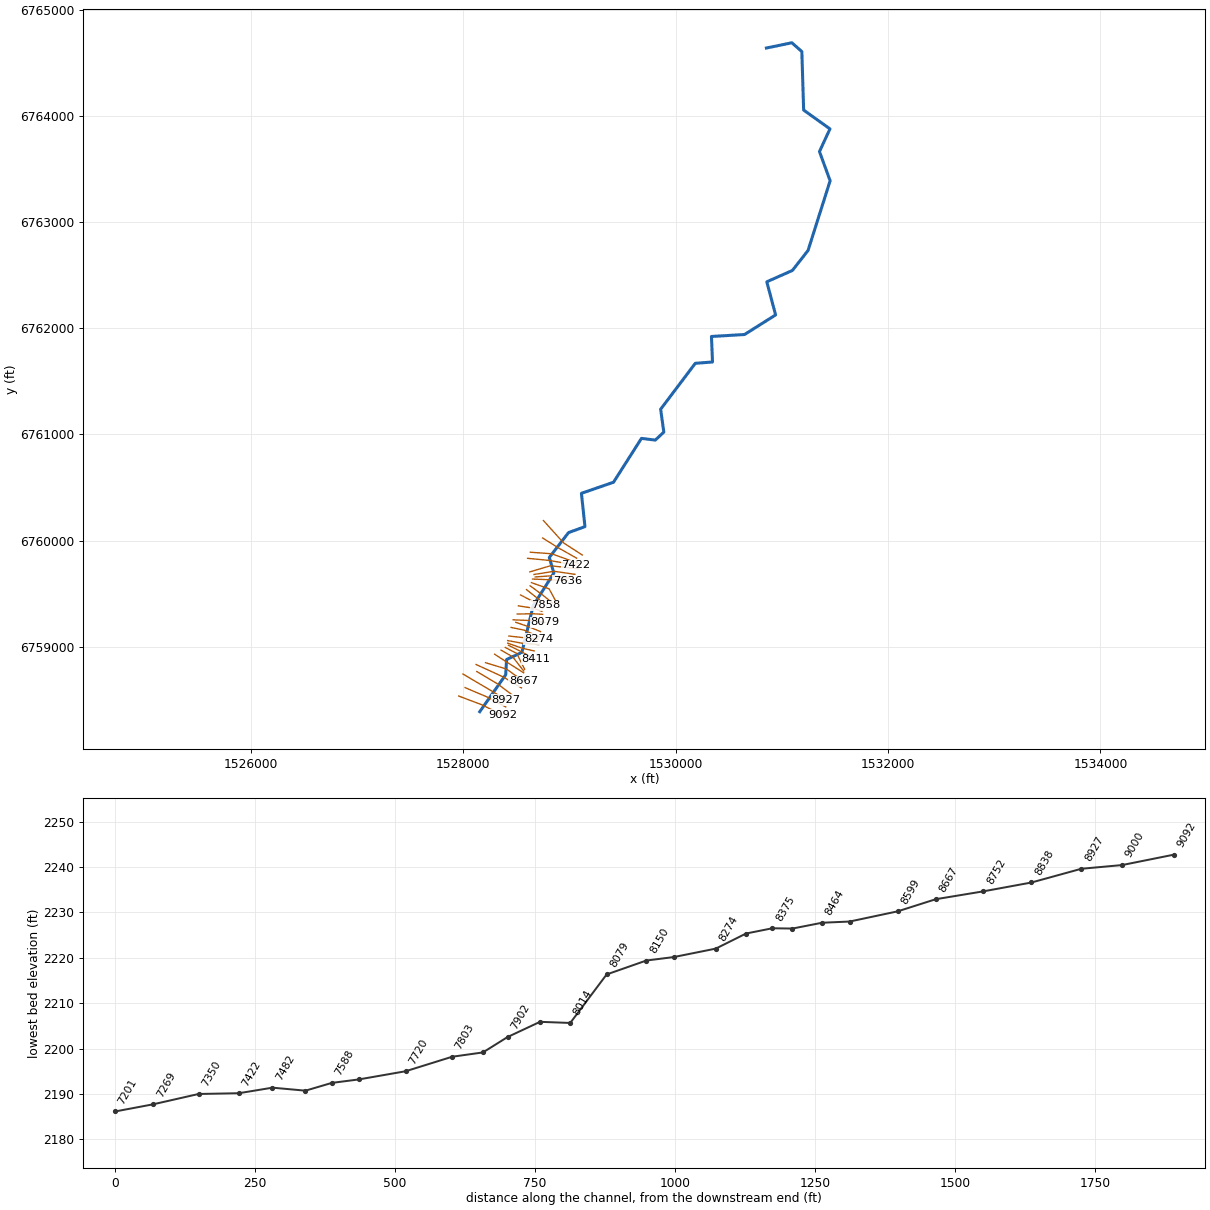
--- Elm 76.prj (project) ---

Proj Title=Elm 76 Base Level Engineering
Current Plan=p01
Default Exp/Contr=0.3,0.1
English Units
Geom File=g01
Flow File=f01
Plan File=p01
BEGIN DESCRIPTION:
Elm 76
END DESCRIPTION:

--- Elm 76.p01 (plan) ---

Plan Title=Multiple Run
Short Identifier=Multiple
Geom File=g01
Flow File=f01
Subcritical Flow
K Sum by GR= 0
Std Step Tol= 0.01
Critical Tol= 0.01
Num of Std Step Trials= 20
Max Error Tol= 0.3
Flow Tol Ratio= 0.001
Split Flow NTrial= 30
Split Flow Tol= 0.02
Split Flow Ratio= 0.02
Log Output Level= 0
Friction Slope Method= 1
Unsteady Friction Slope Method= 2
Unsteady Bridges Friction Slope Method= 1
Parabolic Critical Depth
Global Vel Dist=  1 , 1 , 1
Global Log Level= 0
CheckData=True
Encroach Param= -1, 0, 0, 0
BEGIN DESCRIPTION:
Multiple Run
END DESCRIPTION:

--- Elm 76.f01 (steady flow) ---

Flow Title=Multiple
Number of Profiles=7
Profile Names=10-year,25-year,50-year,1pct_min,100-year,1pct_plu,500-year
River Rch & RM= Elm 76,Reach-1,9092
     267     378     471     365     585     805     915
River Rch & RM= Elm 76,Reach-1,1834
     407     590     748     589     944    1300    1520
Boundary for River Rch & Prof#=Elm 76,Reach-1,1
Up Type=0
Dn Type=3
Dn Slope=0.005
Boundary for River Rch & Prof#=Elm 76,Reach-1,2
Up Type=0
Dn Type=3
Dn Slope=0.005
Boundary for River Rch & Prof#=Elm 76,Reach-1,3
Up Type=0
Dn Type=3
Dn Slope=0.005
Boundary for River Rch & Prof#=Elm 76,Reach-1,4
Up Type=0
Dn Type=3
Dn Slope=0.005
Boundary for River Rch & Prof#=Elm 76,Reach-1,5
Up Type=0
Dn Type=3
Dn Slope=0.005
Boundary for River Rch & Prof#=Elm 76,Reach-1,6
Up Type=0
Dn Type=3
Dn Slope=0.005
Boundary for River Rch & Prof#=Elm 76,Reach-1,7
Up Type=0
Dn Type=3
Dn Slope=0.005

--- Elm 76.g01 (geometry) ---

Geom Title=Existing Conditions

River Reach=Elm 76,Reach-1
Reach XY= 30
      1528155.00      6758388.00      1528399.53      6758735.56
      1528408.07      6758879.72      1528551.94      6758946.28
      1528658.54      6759386.53      1528853.18      6759694.12
      1528810.09      6759840.30      1528991.35      6760074.74
      1529146.01      6760130.93      1529112.69      6760444.57
      1529414.70      6760548.77      1529678.18      6760961.96
      1529808.44      6760945.82      1529888.71      6761021.22
      1529858.74      6761236.44      1530184.93      6761668.72
      1530347.31      6761681.43      1530337.34      6761921.59
      1530649.14      6761940.07      1530941.50      6762124.59
      1530858.52      6762436.54      1531099.56      6762543.19
      1531247.14      6762731.83      1531455.00      6763388.00
      1531354.51      6763663.04      1531453.57      6763876.40
      1531205.56      6764053.58      1531188.59      6764604.80
      1531094.39      6764687.41      1530855.00      6764638.00

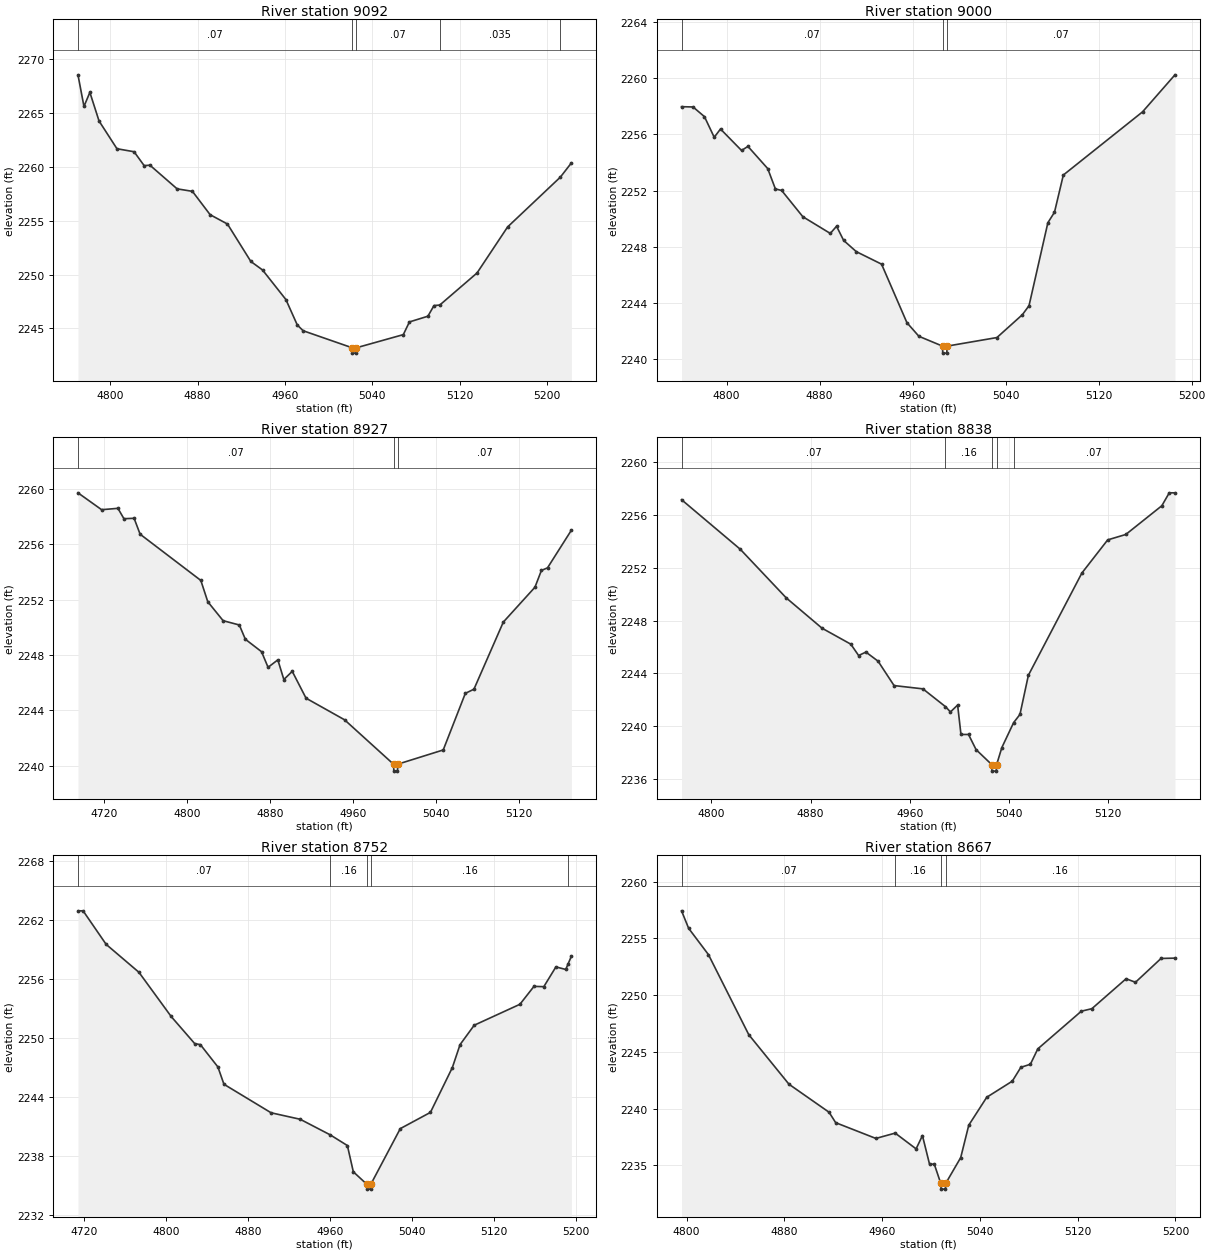
Type RM Length L Ch R = 1,9092,92,92,92
BEGIN DESCRIPTION:
Elm 76 9092.177
END DESCRIPTION:
XS GIS Cut Line= 3
      1527956.91      6758535.75      1528171.62      6758454.69
      1528371.13      6758356.63
#Sta/Elev= 30
  4770.5 2268.57  4776.0 2265.63  4781.4 2266.94  4789.8 2264.28  4806.2 2261.70
  4821.9 2261.42  4831.1 2260.13  4836.4 2260.17  4861.3 2257.97  4875.3 2257.74
  4891.5 2255.57  4907.4 2254.70  4928.8 2251.22  4939.5 2250.43  4960.9 2247.68
  4971.3 2245.32  4976.7 2244.78  5021.5 2243.20  5021.7 2242.70  5025.2 2242.70
  5025.5 2243.20  5068.4 2244.42  5074.0 2245.60  5090.9 2246.13  5096.5 2247.12
  5101.8 2247.17  5135.9 2250.15  5163.9 2254.43  5212.2 2259.06  5222.3 2260.38
#Mann=5,-1,0
  4770.5    0.07       0  5021.5    0.07       0  5025.5    0.07       0
  5101.8   0.035       0  5212.2    0.07       0
Bank Sta=5021.5,5025.5
Exp/Cntr=0.3,0.1

Type RM Length L Ch R = 1,9000,73,73,73
BEGIN DESCRIPTION:
Elm 76 8999.64
END DESCRIPTION:
XS GIS Cut Line= 3
      1528016.84      6758615.16      1528232.96      6758522.73
      1528399.54      6758432.93
#Sta/Elev= 30
  4761.3 2257.98  4771.2 2257.96  4781.0 2257.27  4789.4 2255.80  4794.8 2256.39
  4812.9 2254.86  4818.4 2255.15  4835.4 2253.57  4842.0 2252.12  4847.4 2252.01
  4865.6 2250.14  4889.2 2248.95  4894.6 2249.46  4900.7 2248.45  4911.6 2247.65
  4933.3 2246.76  4955.1 2242.59  4965.4 2241.62  4985.7 2240.92  4985.9 2240.42
  4989.4 2240.42  4989.7 2240.92  5032.5 2241.53  5054.4 2243.16  5060.1 2243.80
  5076.3 2249.71  5082.0 2250.46  5089.6 2253.11  5157.7 2257.61  5185.6 2260.25
#Mann=3,-1,0
  4761.3    0.07       0  4985.7    0.07       0  4989.7    0.07       0
Bank Sta=4985.7,4989.7
Exp/Cntr=0.3,0.1

Type RM Length L Ch R = 1,8927,89,89,89
BEGIN DESCRIPTION:
Elm 76 8926.8
END DESCRIPTION:
XS GIS Cut Line= 3
      1527997.27      6758742.79      1528261.60      6758586.53
      1528404.87      6758497.96
#Sta/Elev= 30
  4694.7 2259.71  4717.5 2258.49  4733.2 2258.59  4739.0 2257.84  4748.8 2257.87
  4754.6 2256.72  4813.1 2253.38  4819.8 2251.84  4834.6 2250.47  4850.2 2250.16
  4856.0 2249.13  4871.6 2248.23  4877.9 2247.10  4887.3 2247.64  4893.1 2246.22
  4901.2 2246.81  4914.5 2244.87  4951.6 2243.31  4998.8 2240.10  4999.1 2239.60
  5002.6 2239.60  5002.8 2240.10  5046.7 2241.13  5068.0 2245.22  5076.3 2245.52
  5104.6 2250.37  5135.1 2252.89  5141.3 2254.10  5147.2 2254.29  5170.2 2257.01
#Mann=3,-1,0
  4694.7    0.07       0  4998.8    0.07       0  5002.8    0.07       0
Bank Sta=4998.8,5002.8
Exp/Cntr=0.3,0.1

Type RM Length L Ch R = 1,8838,86,86,86
BEGIN DESCRIPTION:
Elm 76 8838.26
END DESCRIPTION:
XS GIS Cut Line= 3
      1528127.51      6758766.21      1528322.80      6758650.33
      1528459.54      6758547.45
#Sta/Elev= 30
  4775.9 2257.17  4823.3 2253.41  4860.4 2249.72  4889.3 2247.42  4912.5 2246.21
  4918.8 2245.35  4924.7 2245.61  4934.5 2244.92  4947.4 2243.07  4970.7 2242.82
  4988.9 2241.47  4992.9 2241.07  4998.7 2241.59  5001.4 2239.36  5007.5 2239.36
  5013.6 2238.21  5026.2 2237.08  5026.4 2236.58  5029.9 2236.58  5030.2 2237.08
  5034.4 2238.37  5043.9 2240.26  5049.0 2240.88  5055.8 2243.85  5099.0 2251.61
  5119.8 2254.12  5134.4 2254.53  5163.5 2256.71  5169.5 2257.69  5174.1 2257.69
#Mann=5,-1,0
  4775.9    0.07       0  4988.9    0.16       0  5026.2    0.07       0
  5030.2    0.16       0  5043.9    0.07       0
Bank Sta=5026.2,5030.2
Exp/Cntr=0.3,0.1

Type RM Length L Ch R = 1,8752,85,85,85
BEGIN DESCRIPTION:
Elm 76 8752.3
END DESCRIPTION:
XS GIS Cut Line= 3
      1528120.97      6758832.63      1528378.79      6758714.13
      1528547.96      6758612.11
#Sta/Elev= 30
  4714.1 2262.92  4719.1 2262.92  4741.6 2259.51  4773.6 2256.67  4805.0 2252.18
  4828.0 2249.42  4833.5 2249.32  4850.6 2247.05  4856.5 2245.29  4902.5 2242.39
  4930.9 2241.73  4960.1 2240.15  4976.9 2239.06  4982.7 2236.39  4995.8 2235.13
  4996.1 2234.63  4999.6 2234.63  4999.8 2235.13  5028.5 2240.78  5057.9 2242.43
  5079.3 2246.99  5086.8 2249.32  5100.6 2251.29  5145.2 2253.42  5158.9 2255.24
  5168.5 2255.21  5180.3 2257.22  5189.9 2256.96  5192.3 2257.55  5195.4 2258.31
#Mann=5,-1,0
  4714.1    0.07       0  4960.1    0.16       0  4995.8    0.07       0
  4999.8    0.16       0  5192.3    0.07       0
Bank Sta=4995.8,4999.8
Exp/Cntr=0.3,0.1

Type RM Length L Ch R = 1,8667,68,68,68
BEGIN DESCRIPTION:
Elm 76 8667.32
END DESCRIPTION:
XS GIS Cut Line= 3
      1528209.49      6758849.56      1528407.44      6758789.65
      1528567.57      6758675.09
#Sta/Elev= 30
  4795.9 2257.44  4801.7 2255.90  4817.9 2253.58  4850.9 2246.52  4883.8 2242.15
  4916.6 2239.68  4922.0 2238.76  4954.9 2237.37  4970.7 2237.84  4987.8 2236.45
  4993.0 2237.62  4998.8 2235.10  5002.7 2235.10  5008.0 2233.40  5008.3 2232.90
  5011.8 2232.90  5012.0 2233.40  5024.3 2235.68  5030.9 2238.54  5045.6 2241.00
  5066.5 2242.42  5073.5 2243.64  5081.3 2243.91  5087.4 2245.27  5123.0 2248.59
  5131.6 2248.81  5159.6 2251.45  5167.3 2251.14  5188.2 2253.24  5199.6 2253.27
#Mann=4,-1,0
  4795.9    0.07       0  4970.7    0.16       0  5008.0    0.07       0
  5012.0    0.16       0
Bank Sta=5008,5012
Exp/Cntr=0.3,0.1

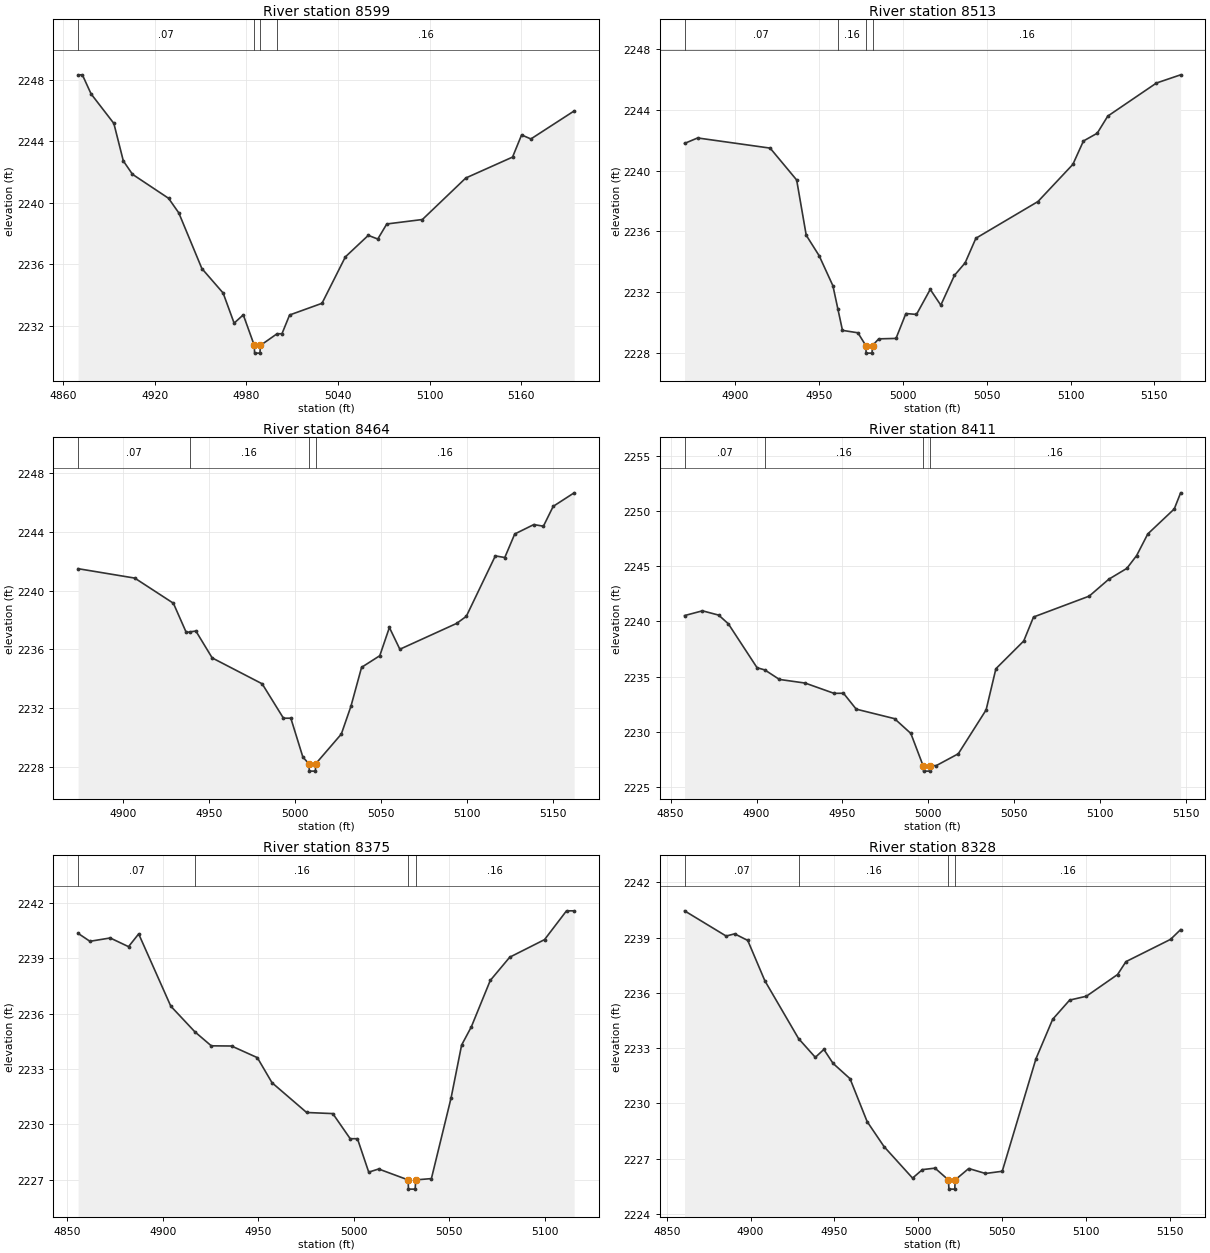
Type RM Length L Ch R = 1,8599,86,86,86
BEGIN DESCRIPTION:
Elm 76 8599.325
END DESCRIPTION:
XS GIS Cut Line= 3
      1528295.39      6758929.29      1528404.49      6758858.43
      1528568.90      6758754.50
#Sta/Elev= 30
  4869.9 2248.33  4872.7 2248.33  4878.4 2247.09  4893.3 2245.17  4899.5 2242.73
  4905.5 2241.86  4929.1 2240.30  4935.8 2239.35  4950.9 2235.73  4964.8 2234.14
  4972.0 2232.18  4978.0 2232.72  4985.2 2230.73  4985.4 2230.23  4988.9 2230.23
  4989.2 2230.73  5000.1 2231.49  5003.3 2231.49  5008.3 2232.71  5029.5 2233.47
  5044.8 2236.49  5059.8 2237.89  5066.0 2237.65  5071.9 2238.63  5095.2 2238.92
  5123.6 2241.62  5154.2 2242.98  5160.1 2244.42  5166.2 2244.16  5194.5 2245.98
#Mann=4,-1,0
  4869.9    0.07       0  4985.2    0.07       0  4989.2    0.07       0
  5000.1    0.16       0
Bank Sta=4985.2,4989.2
Exp/Cntr=0.3,0.1

Type RM Length L Ch R = 1,8513,49,49,49
BEGIN DESCRIPTION:
Elm 76 8512.91
END DESCRIPTION:
XS GIS Cut Line= 3
      1528355.35      6758968.04      1528464.73      6758905.54
      1528568.95      6758771.72
#Sta/Elev= 30
  4870.0 2241.80  4877.8 2242.16  4921.0 2241.49  4936.8 2239.39  4942.5 2235.75
  4950.2 2234.40  4958.4 2232.42  4961.4 2230.87  4964.1 2229.48  4973.3 2229.32
  4978.0 2228.48  4978.2 2227.98  4981.7 2227.98  4982.0 2228.48  4985.7 2228.92
  4996.0 2228.95  5001.9 2230.59  5008.2 2230.53  5016.4 2232.18  5022.7 2231.14
  5030.8 2233.10  5037.2 2233.93  5043.6 2235.55  5080.6 2237.97  5101.4 2240.42
  5107.7 2241.96  5115.9 2242.47  5122.2 2243.60  5151.2 2245.78  5165.6 2246.32
#Mann=4,-1,0
  4870.0    0.07       0  4961.4    0.16       0  4978.0    0.07       0
  4982.0    0.16       0
Bank Sta=4978,4982
Exp/Cntr=0.3,0.1

Type RM Length L Ch R = 1,8464,53,53,53
BEGIN DESCRIPTION:
Elm 76 8463.81
END DESCRIPTION:
XS GIS Cut Line= 3
      1528395.68      6758992.80      1528503.79      6758936.79
      1528578.02      6758787.03
#Sta/Elev= 30
  4873.6 2241.49  4906.6 2240.85  4929.1 2239.14  4936.6 2237.15  4938.7 2237.19
  4942.2 2237.25  4951.7 2235.42  4980.8 2233.66  4993.2 2231.32  4997.5 2231.32
  5004.5 2228.68  5008.0 2228.22  5008.3 2227.72  5011.8 2227.72  5012.0 2228.22
  5026.9 2230.24  5032.5 2232.13  5038.7 2234.78  5049.3 2235.57  5054.9 2237.49
  5061.0 2236.01  5094.1 2237.77  5099.7 2238.25  5116.6 2242.36  5122.1 2242.25
  5127.9 2243.85  5139.0 2244.49  5144.6 2244.38  5150.3 2245.73  5162.5 2246.65
#Mann=4,-1,0
  4873.6    0.07       0  4938.7    0.16       0  5008.0    0.07       0
  5012.0    0.16       0
Bank Sta=5008,5012
Exp/Cntr=0.3,0.1

Type RM Length L Ch R = 1,8411,36,36,36
BEGIN DESCRIPTION:
Elm 76 8410.83
END DESCRIPTION:
XS GIS Cut Line= 3
      1528425.67      6759013.61      1528553.27      6758949.81
      1528681.77      6758880.42
#Sta/Elev= 30
  4858.1 2240.52  4868.5 2240.95  4878.0 2240.56  4883.6 2239.77  4900.3 2235.80
  4904.8 2235.60  4913.3 2234.74  4928.3 2234.41  4945.1 2233.48  4950.6 2233.49
  4958.0 2232.05  4980.3 2231.19  4989.8 2229.85  4996.9 2226.94  4997.2 2226.44
  5000.7 2226.44  5000.9 2226.94  5004.6 2226.94  5017.4 2228.01  5033.6 2231.98
  5039.3 2235.71  5055.5 2238.22  5061.2 2240.39  5093.6 2242.28  5105.0 2243.81
  5115.5 2244.79  5121.2 2245.95  5127.7 2247.91  5143.1 2250.17  5146.8 2251.63
#Mann=4,-1,0
  4858.1    0.07       0  4904.8    0.16       0  4996.9    0.07       0
  5000.9    0.16       0
Bank Sta=4996.9,5000.9
Exp/Cntr=0.3,0.1

Type RM Length L Ch R = 1,8375,47,47,47
BEGIN DESCRIPTION:
Elm 76 8375.15
END DESCRIPTION:
XS GIS Cut Line= 3
      1528419.16      6759033.14      1528557.18      6758984.97
      1528667.87      6758960.22
#Sta/Elev= 30
  4855.7 2240.35  4861.9 2239.92  4872.5 2240.10  4882.1 2239.63  4887.4 2240.32
  4904.2 2236.41  4916.8 2235.02  4925.4 2234.26  4936.0 2234.25  4949.5 2233.62
  4957.2 2232.26  4975.3 2230.65  4989.0 2230.59  4998.1 2229.23  5001.9 2229.23
  5007.8 2227.42  5013.0 2227.59  5028.4 2227.00  5028.6 2226.50  5032.1 2226.50
  5032.4 2227.00  5040.6 2227.07  5050.9 2231.44  5056.4 2234.30  5061.5 2235.29
  5071.4 2237.80  5081.6 2239.06  5099.8 2240.01  5111.3 2241.57  5115.3 2241.57
#Mann=4,-1,0
  4855.7    0.07       0  4916.8    0.16       0  5028.4    0.07       0
  5032.4    0.16       0
Bank Sta=5028.4,5032.4
Exp/Cntr=0.3,0.1

Type RM Length L Ch R = 1,8328,54,54,54
BEGIN DESCRIPTION:
Elm 76 8327.73
END DESCRIPTION:
XS GIS Cut Line= 3
      1528417.89      6759057.88      1528553.27      6759033.14
      1528711.02      6759020.21
#Sta/Elev= 30
  4860.6 2240.46  4885.4 2239.09  4890.5 2239.21  4898.3 2238.85  4908.5 2236.66
  4928.6 2233.52  4938.6 2232.50  4943.7 2232.93  4949.2 2232.17  4959.3 2231.34
  4969.5 2229.01  4979.6 2227.65  4996.6 2225.94  5002.5 2226.40  5010.0 2226.48
  5018.0 2225.84  5018.3 2225.34  5021.8 2225.34  5022.0 2225.84  5030.1 2226.46
  5040.1 2226.19  5050.1 2226.31  5070.2 2232.42  5080.2 2234.57  5090.3 2235.61
  5100.3 2235.82  5118.9 2237.00  5123.9 2237.70  5150.5 2238.91  5156.5 2239.44
#Mann=4,-1,0
  4860.6    0.07       0  4928.6    0.16       0  5018.0    0.07       0
  5022.0    0.16       0
Bank Sta=5018,5022
Exp/Cntr=0.3,0.1

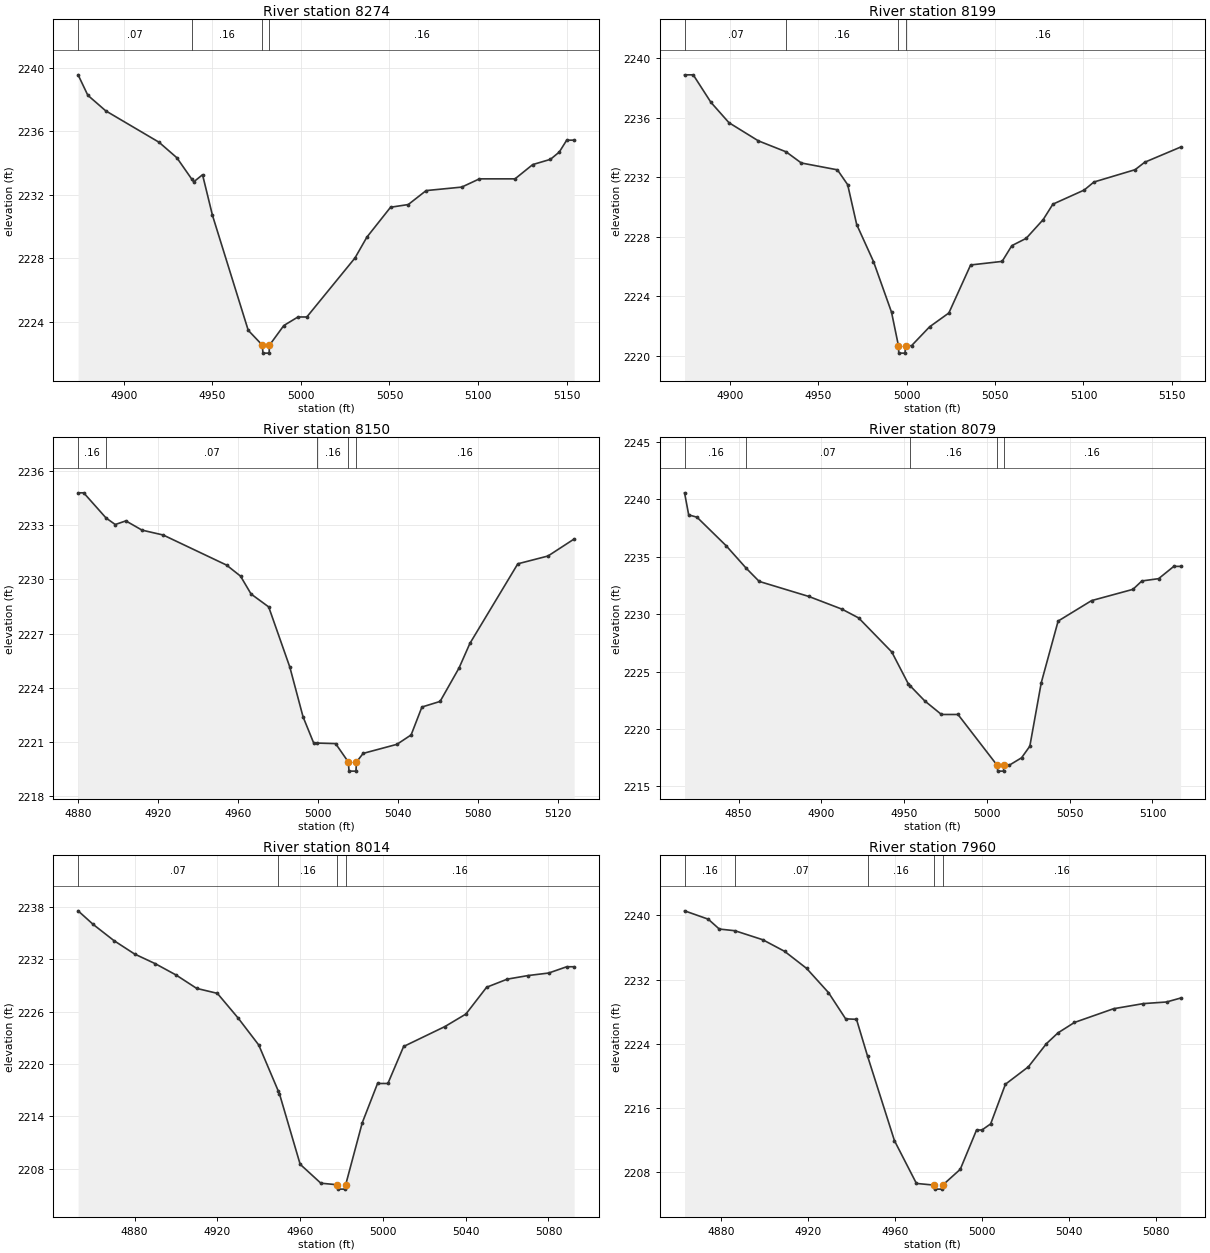
Type RM Length L Ch R = 1,8274,75,75,75
BEGIN DESCRIPTION:
Elm 76 8274.06
END DESCRIPTION:
XS GIS Cut Line= 3
      1528429.54      6759100.86      1528555.87      6759086.53
      1528708.26      6759072.20
#Sta/Elev= 30
  4874.1 2239.57  4879.6 2238.28  4889.7 2237.30  4919.8 2235.32  4929.9 2234.34
  4938.2 2233.01  4939.4 2232.82  4944.4 2233.27  4950.0 2230.71  4970.2 2223.46
  4978.2 2222.52  4978.5 2222.02  4982.0 2222.02  4982.2 2222.52  4990.3 2223.76
  4998.3 2224.30  5003.3 2224.30  5030.5 2228.02  5037.2 2229.33  5050.6 2231.22
  5060.6 2231.39  5070.7 2232.27  5090.8 2232.49  5100.8 2233.01  5120.9 2233.01
  5130.9 2233.91  5140.9 2234.24  5145.9 2234.70  5150.1 2235.45  5154.3 2235.45
#Mann=4,-1,0
  4874.1    0.07       0  4938.2    0.16       0  4978.2    0.07       0
  4982.2    0.16       0
Bank Sta=4978.2,4982.2
Exp/Cntr=0.3,0.1

Type RM Length L Ch R = 1,8199,49,49,49
BEGIN DESCRIPTION:
Elm 76 8199.44
END DESCRIPTION:
XS GIS Cut Line= 3
      1528450.37      6759181.59      1528571.50      6759156.84
      1528714.70      6759093.05
#Sta/Elev= 30
  4874.5 2238.88  4879.4 2238.88  4889.4 2237.03  4899.6 2235.66  4916.2 2234.44
  4931.9 2233.70  4940.5 2232.95  4960.9 2232.49  4966.7 2231.49  4971.8 2228.81
  4981.3 2226.32  4991.5 2222.91  4995.4 2220.66  4995.6 2220.16  4999.1 2220.16
  4999.4 2220.66  5002.8 2220.66  5013.0 2221.93  5023.9 2222.86  5036.2 2226.09
  5054.0 2226.33  5059.5 2227.39  5067.6 2227.88  5077.2 2229.14  5082.7 2230.18
  5100.4 2231.13  5105.9 2231.67  5129.2 2232.50  5134.6 2233.00  5154.9 2234.02
#Mann=4,-1,0
  4874.5    0.07       0  4931.9    0.16       0  4995.4    0.07       0
  4999.4    0.16       0
Bank Sta=4995.4,4999.4
Exp/Cntr=0.3,0.1

Type RM Length L Ch R = 1,8150,71,71,71
BEGIN DESCRIPTION:
Elm 76 8149.86
END DESCRIPTION:
XS GIS Cut Line= 3
      1528494.68      6759229.76      1528613.17      6759189.39
      1528727.13      6759142.77
#Sta/Elev= 30
  4879.9 2234.77  4882.7 2234.77  4893.9 2233.38  4898.5 2233.02  4903.8 2233.22
  4911.9 2232.71  4922.5 2232.44  4954.2 2230.78  4961.2 2230.17  4966.5 2229.18
  4975.3 2228.47  4985.9 2225.14  4992.5 2222.40  4997.8 2220.96  4999.4 2220.95
  5008.8 2220.92  5015.2 2219.90  5015.5 2219.40  5019.0 2219.40  5019.2 2219.90
  5022.6 2220.38  5039.5 2220.88  5046.6 2221.40  5052.0 2222.94  5061.1 2223.25
  5070.6 2225.10  5076.0 2226.45  5100.0 2230.85  5115.1 2231.28  5128.2 2232.22
#Mann=5,-1,0
  4879.9    0.16       0  4893.9    0.07       0  4999.4    0.16       0
  5015.2    0.07       0  5019.2    0.16       0
Bank Sta=5015.2,5019.2
Exp/Cntr=0.3,0.1

Type RM Length L Ch R = 1,8079,65,65,65
BEGIN DESCRIPTION:
Elm 76 8078.5
END DESCRIPTION:
XS GIS Cut Line= 3
      1528469.92      6759253.20      1528661.34      6759245.38
      1528768.13      6759228.45
#Sta/Elev= 30
  4817.3 2240.55  4819.8 2238.63  4824.8 2238.43  4842.4 2235.95  4854.6 2233.98
  4862.4 2232.84  4892.4 2231.53  4912.5 2230.42  4922.5 2229.66  4942.5 2226.70
  4952.5 2223.92  4953.7 2223.74  4962.5 2222.43  4972.5 2221.26  4982.5 2221.26
  5006.2 2216.83  5006.5 2216.33  5010.0 2216.33  5010.2 2216.83  5013.3 2216.83
  5020.9 2217.49  5025.9 2218.50  5032.8 2224.02  5043.0 2229.39  5063.2 2231.17
  5088.2 2232.15  5093.6 2232.88  5103.7 2233.08  5112.9 2234.15  5117.0 2234.15
#Mann=5,-1,0
  4817.3    0.16       0  4854.6    0.07       0  4953.7    0.16       0
  5006.2    0.07       0  5010.2    0.16       0
Bank Sta=5006.2,5010.2
Exp/Cntr=0.3,0.1

Type RM Length L Ch R = 1,8014,54,54,54
BEGIN DESCRIPTION:
Elm 76 8013.55
END DESCRIPTION:
XS GIS Cut Line= 3
      1528507.74      6759307.88      1528654.83      6759310.49
      1528747.27      6759305.28
#Sta/Elev= 30
  4852.7 2237.55  4860.0 2235.99  4870.0 2234.14  4880.0 2232.60  4890.0 2231.49
  4900.0 2230.20  4910.0 2228.66  4920.0 2228.09  4930.0 2225.27  4940.0 2222.17
  4949.5 2216.86  4950.0 2216.58  4960.0 2208.50  4970.0 2206.33  4978.0 2206.15
  4978.2 2205.65  4981.7 2205.65  4982.0 2206.15  4990.0 2213.25  4997.4 2217.76
  5002.4 2217.76  5010.0 2222.00  5030.0 2224.29  5040.1 2225.72  5050.1 2228.79
  5060.1 2229.72  5070.1 2230.13  5080.1 2230.42  5088.8 2231.14  5092.4 2231.14
#Mann=4,-1,0
  4852.7    0.07       0  4949.5    0.16       0  4978.0    0.07       0
  4982.0    0.16       0
Bank Sta=4978,4982
Exp/Cntr=0.3,0.1

Type RM Length L Ch R = 1,7960,58,58,58
BEGIN DESCRIPTION:
Elm 76 7960.15
END DESCRIPTION:
XS GIS Cut Line= 3
      1528519.45      6759384.70      1528654.83      6759363.87
      1528741.14      6759333.41
#Sta/Elev= 30
  4863.0 2240.58  4873.9 2239.54  4879.0 2238.31  4886.2 2238.10  4899.0 2236.98
  4909.1 2235.53  4919.2 2233.41  4929.3 2230.39  4937.2 2227.12  4942.2 2227.06
  4947.3 2222.47  4959.7 2211.93  4969.8 2206.61  4977.9 2206.40  4978.2 2205.90
  4981.7 2205.90  4981.9 2206.40  4990.0 2208.37  4997.5 2213.27  5000.0 2213.27
  5004.0 2214.03  5010.8 2218.97  5021.4 2221.15  5029.7 2224.03  5035.0 2225.37
  5042.6 2226.67  5060.6 2228.38  5074.4 2229.02  5085.0 2229.22  5091.5 2229.71
#Mann=5,-1,0
  4863.0    0.16       0  4886.2    0.07       0  4947.3    0.16       0
  4977.9    0.07       0  4981.9    0.16       0
Bank Sta=4977.9,4981.9
Exp/Cntr=0.3,0.1

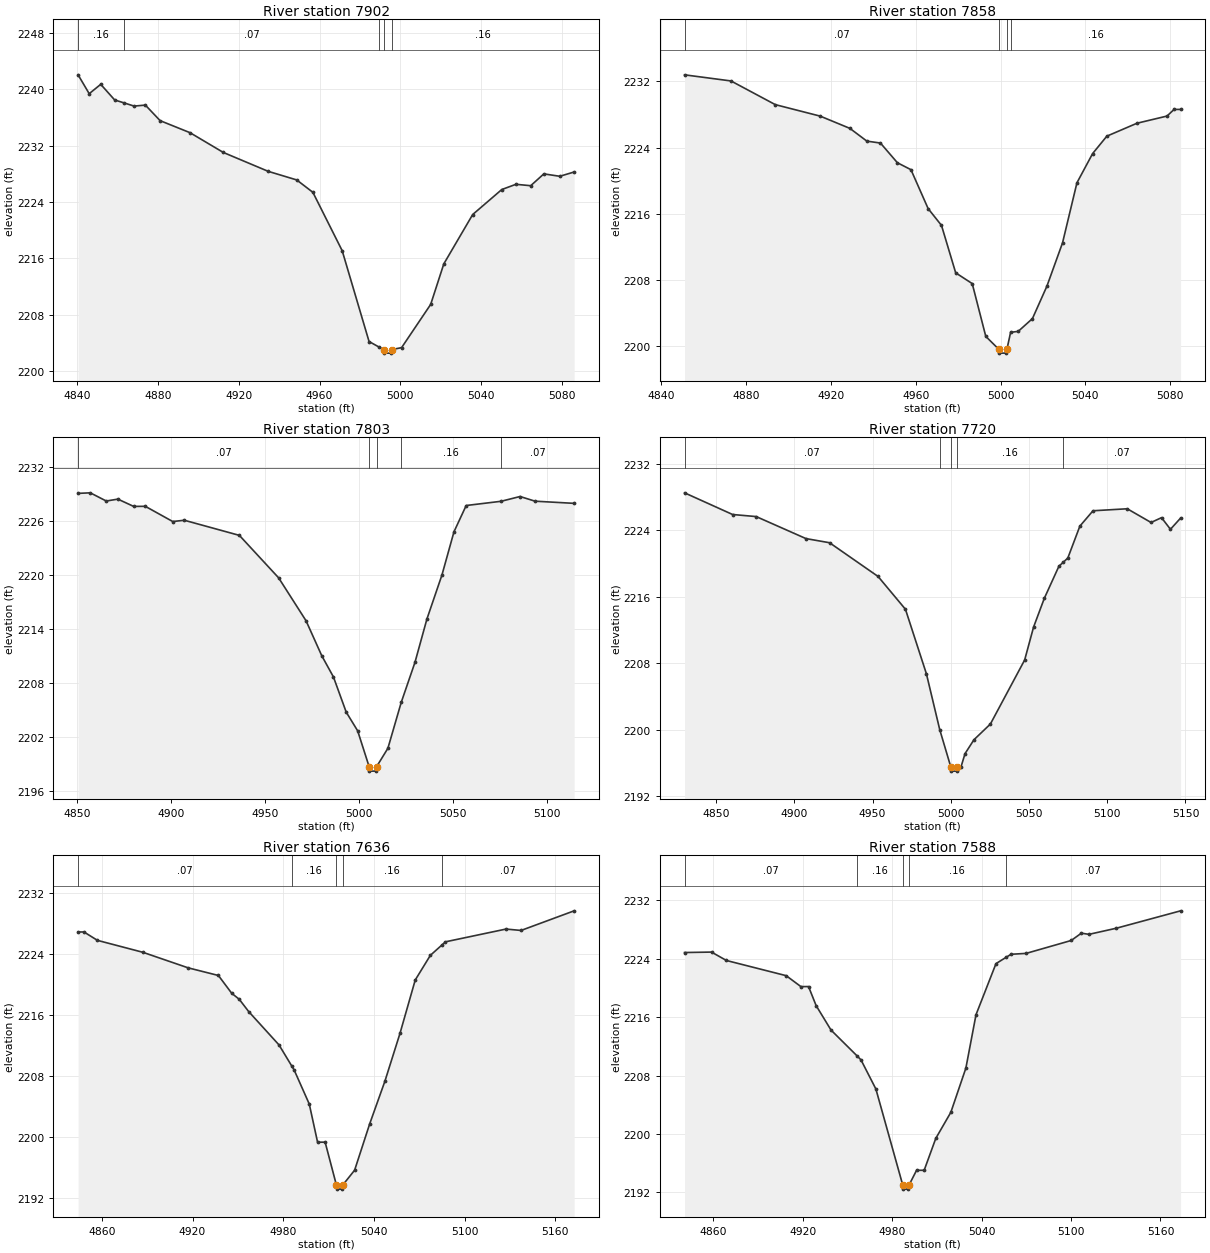
Type RM Length L Ch R = 1,7902,44,44,44
BEGIN DESCRIPTION:
Elm 76 7901.76
END DESCRIPTION:
XS GIS Cut Line= 3
      1528538.96      6759487.57      1528682.18      6759413.35
      1528747.28      6759359.97
#Sta/Elev= 30
  4840.5 2242.08  4846.0 2239.40  4851.7 2240.73  4858.6 2238.51  4863.4 2238.08
  4868.2 2237.64  4873.8 2237.78  4881.1 2235.57  4895.9 2233.86  4912.4 2231.05
  4934.6 2228.37  4948.7 2227.15  4956.7 2225.39  4971.2 2217.10  4984.5 2204.20
  4989.2 2203.45  4991.7 2203.05  4992.0 2202.55  4995.5 2202.55  4995.7 2203.05
  5000.6 2203.33  5015.0 2209.47  5021.5 2215.23  5035.8 2222.24  5050.2 2225.79
  5057.2 2226.53  5064.5 2226.33  5071.0 2228.01  5078.9 2227.67  5086.0 2228.28
#Mann=5,-1,0
  4840.5    0.16       0  4863.4    0.07       0  4989.2    0.16       0
  4991.7    0.07       0  4995.7    0.16       0
Bank Sta=4991.7,4995.7
Exp/Cntr=0.3,0.1

Type RM Length L Ch R = 1,7858,55,55,55
BEGIN DESCRIPTION:
Elm 76 7857.66
END DESCRIPTION:
XS GIS Cut Line= 3
      1528594.94      6759538.35      1528716.03      6759442.00
      1528774.62      6759388.62
#Sta/Elev= 30
  4850.9 2232.78  4872.8 2232.04  4893.7 2229.18  4914.9 2227.79  4928.9 2226.31
  4936.9 2224.77  4943.3 2224.54  4951.3 2222.16  4957.7 2221.32  4965.8 2216.62
  4972.1 2214.59  4978.8 2208.86  4986.6 2207.56  4993.0 2201.18  4999.0 2199.66
  4999.2 2199.16  5002.7 2199.16  5003.0 2199.66  5004.7 2201.67  5008.3 2201.79
  5015.0 2203.33  5021.8 2207.23  5029.2 2212.48  5036.0 2219.74  5043.4 2223.27
  5050.1 2225.37  5064.3 2226.93  5078.5 2227.80  5081.8 2228.60  5084.9 2228.60
#Mann=4,-1,0
  4850.9    0.07       0  4999.0    0.07       0  5003.0    0.07       0
  5004.7    0.16       0
Bank Sta=4999,5003
Exp/Cntr=0.3,0.1

Type RM Length L Ch R = 1,7803,83,83,83
BEGIN DESCRIPTION:
Elm 76 7802.63
END DESCRIPTION:
XS GIS Cut Line= 3
      1528630.13      6759573.48      1528749.88      6759484.97
      1528839.91      6759412.95
#Sta/Elev= 30
  4850.5 2229.09  4857.0 2229.15  4865.5 2228.24  4871.7 2228.45  4880.1 2227.64
  4886.3 2227.65  4900.9 2225.96  4907.1 2226.10  4936.4 2224.42  4957.3 2219.70
  4971.9 2214.93  4980.3 2211.03  4986.5 2208.68  4993.3 2204.77  4999.4 2202.69
  5005.5 2198.71  5005.7 2198.21  5009.2 2198.21  5009.5 2198.71  5015.5 2200.75
  5022.6 2205.85  5029.9 2210.29  5036.3 2215.13  5044.3 2220.02  5050.7 2224.82
  5057.2 2227.74  5075.8 2228.21  5085.9 2228.74  5093.9 2228.22  5114.7 2227.98
#Mann=5,-1,0
  4850.5    0.07       0  5005.5    0.07       0  5009.5    0.07       0
  5022.6    0.16       0  5075.8    0.07       0
Bank Sta=5005.5,5009.5
Exp/Cntr=0.3,0.1

Type RM Length L Ch R = 1,7720,84,84,84
BEGIN DESCRIPTION:
Elm 76 7720.09
END DESCRIPTION:
XS GIS Cut Line= 3
      1528641.79      6759603.47      1528808.48      6759544.86
      1528875.35      6759421.40
#Sta/Elev= 30
  4829.8 2228.53  4860.5 2225.92  4875.6 2225.67  4907.4 2223.02  4922.5 2222.52
  4953.5 2218.46  4971.0 2214.51  4984.4 2206.74  4992.9 2200.03  5000.0 2195.52
  5000.2 2195.02  5003.7 2195.02  5004.0 2195.52  5006.5 2195.52  5009.1 2197.13
  5014.8 2198.80  5025.3 2200.69  5047.2 2208.40  5052.9 2212.36  5059.8 2215.84
  5069.1 2219.69  5072.0 2220.19  5074.8 2220.68  5082.5 2224.52  5090.9 2226.37
  5112.8 2226.61  5128.0 2224.96  5134.7 2225.54  5140.4 2224.14  5146.9 2225.49
#Mann=5,-1,0
  4829.8    0.07       0  4992.9    0.16       0  5000.0    0.07       0
  5004.0    0.16       0  5072.0    0.07       0
Bank Sta=5000,5004
Exp/Cntr=0.3,0.1

Type RM Length L Ch R = 1,7636,48,48,48
BEGIN DESCRIPTION:
Elm 76 7635.57
END DESCRIPTION:
XS GIS Cut Line= 3
      1528652.25      6759637.31      1528811.08      6759630.80
      1528980.03      6759623.00
#Sta/Elev= 30
  4844.3 2226.90  4848.2 2226.90  4857.1 2225.80  4887.1 2224.24  4917.1 2222.20
  4937.1 2221.20  4945.9 2218.87  4950.9 2218.08  4957.1 2216.48  4977.2 2212.10
  4985.5 2209.38  4987.2 2208.82  4997.2 2204.36  5002.7 2199.36  5007.7 2199.36
  5015.2 2193.71  5015.5 2193.21  5019.0 2193.21  5019.2 2193.71  5027.2 2195.69
  5037.2 2201.78  5047.2 2207.33  5057.2 2213.61  5067.3 2220.61  5077.3 2223.84
  5084.7 2225.15  5087.3 2225.61  5127.3 2227.28  5137.3 2227.10  5172.4 2229.67
#Mann=5,-1,0
  4844.3    0.07       0  4985.5    0.16       0  5015.2    0.07       0
  5019.2    0.16       0  5084.7    0.07       0
Bank Sta=5015.2,5019.2
Exp/Cntr=0.3,0.1

Type RM Length L Ch R = 1,7588,47,47,47
BEGIN DESCRIPTION:
Elm 76 7588.15
END DESCRIPTION:
XS GIS Cut Line= 3
      1528676.95      6759656.84      1528834.52      6759668.56
      1529007.65      6759643.83
#Sta/Elev= 30
  4840.6 2224.85  4858.7 2224.91  4868.7 2223.76  4908.8 2221.68  4918.7 2220.18
  4923.8 2220.19  4928.9 2217.58  4938.9 2214.23  4956.4 2210.69  4959.0 2210.15
  4969.0 2206.16  4987.1 2192.95  4987.3 2192.45  4990.8 2192.45  4991.1 2192.95
  4996.3 2195.03  5001.4 2195.03  5009.2 2199.40  5019.3 2202.97  5029.4 2209.03
  5036.2 2216.34  5049.6 2223.33  5056.2 2224.17  5059.7 2224.61  5069.8 2224.73
  5100.1 2226.50  5106.9 2227.50  5112.0 2227.34  5130.4 2228.18  5173.5 2230.56
#Mann=5,-1,0
  4840.6    0.07       0  4956.4    0.16       0  4987.1    0.07       0
  4991.1    0.16       0  5056.2    0.07       0
Bank Sta=4987.1,4991.1
Exp/Cntr=0.3,0.1

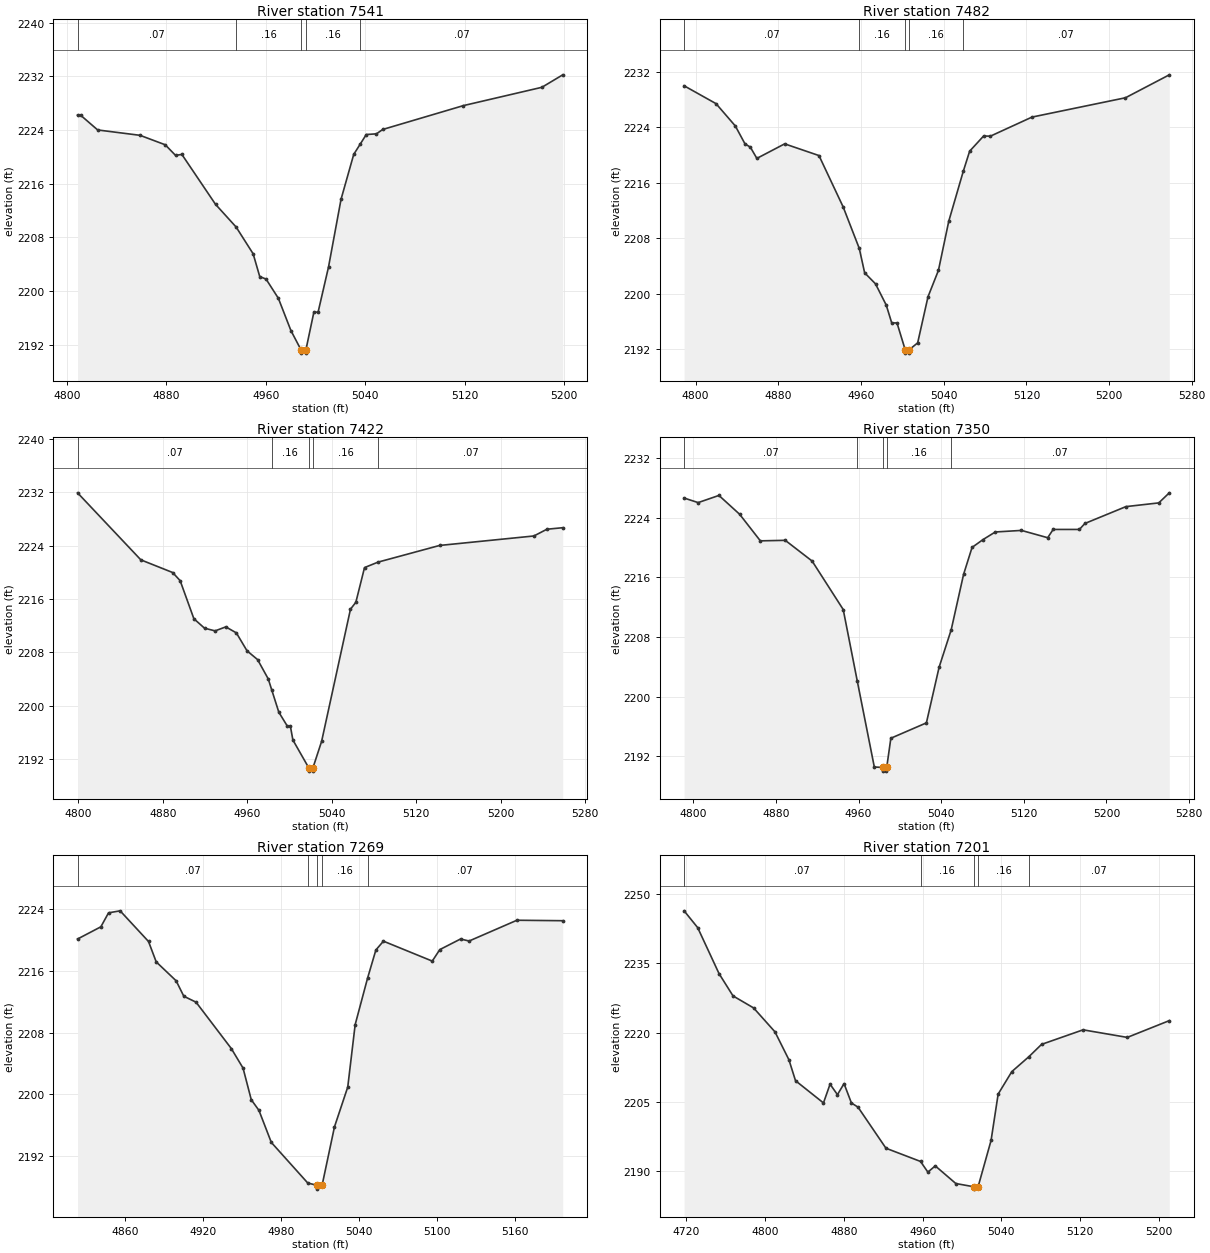
Type RM Length L Ch R = 1,7541,59,59,59
BEGIN DESCRIPTION:
Elm 76 7541.15
END DESCRIPTION:
XS GIS Cut Line= 3
      1528665.27      6759680.28      1528856.66      6759710.23
      1529051.59      6759681.83
#Sta/Elev= 30
  4808.4 2226.23  4810.8 2226.23  4824.6 2224.02  4858.7 2223.22  4879.0 2221.81
  4887.3 2220.23  4892.4 2220.37  4919.5 2212.93  4936.1 2209.54  4949.8 2205.55
  4955.1 2202.16  4960.2 2201.78  4970.1 2198.92  4980.2 2194.11  4988.3 2191.24
  4988.6 2190.74  4992.1 2190.74  4992.3 2191.24  4998.7 2196.85  5002.1 2196.85
  5010.5 2203.59  5020.6 2213.70  5030.8 2220.38  5036.1 2221.93  5040.9 2223.34
  5049.1 2223.44  5054.1 2224.09  5119.1 2227.65  5182.3 2230.38  5199.1 2232.24
#Mann=5,-1,0
  4808.4    0.07       0  4936.1    0.16       0  4988.3    0.07       0
  4992.3    0.16       0  5036.1    0.07       0
Bank Sta=4988.3,4992.3
Exp/Cntr=0.3,0.1

Type RM Length L Ch R = 1,7482,60,60,60
BEGIN DESCRIPTION:
Elm 76 7481.58
END DESCRIPTION:
XS GIS Cut Line= 3
      1528627.50      6759705.02      1528820.20      6759762.31
      1529087.13      6759733.66
#Sta/Elev= 30
  4788.8 2229.98  4819.7 2227.40  4838.4 2224.17  4847.7 2221.60  4852.9 2221.12
  4859.2 2219.50  4886.1 2221.60  4919.3 2219.91  4942.7 2212.50  4958.3 2206.51
  4963.5 2202.99  4974.0 2201.40  4984.4 2198.33  4989.7 2195.76  4994.8 2195.76
  5002.7 2191.90  5003.0 2191.40  5006.5 2191.40  5006.7 2191.90  5014.8 2192.88
  5024.8 2199.53  5034.9 2203.34  5044.9 2210.44  5058.9 2217.62  5065.1 2220.54
  5078.6 2222.73  5085.2 2222.71  5125.4 2225.46  5215.9 2228.25  5258.3 2231.56
#Mann=5,-1,0
  4788.8    0.07       0  4958.3    0.16       0  5002.7    0.07       0
  5006.7    0.16       0  5058.9    0.07       0
Bank Sta=5002.7,5006.7
Exp/Cntr=0.3,0.1

Type RM Length L Ch R = 1,7422,72,72,72
BEGIN DESCRIPTION:
Elm 76 7421.83
END DESCRIPTION:
XS GIS Cut Line= 3
      1528605.39      6759832.62      1528805.87      6759813.09
      1529059.81      6759768.82
#Sta/Elev= 30
  4799.4 2231.91  4859.3 2221.86  4889.4 2219.96  4896.5 2218.74  4909.5 2213.03
  4919.6 2211.61  4929.6 2211.21  4939.7 2211.81  4949.7 2210.91  4959.8 2208.22
  4969.8 2206.90  4979.9 2204.00  4983.1 2202.40  4989.9 2199.01  4997.9 2196.94
  5000.8 2196.94  5003.2 2194.85  5018.2 2190.68  5018.5 2190.18  5022.0 2190.18
  5022.2 2190.68  5030.4 2194.65  5057.7 2214.46  5062.8 2215.50  5071.0 2220.70
  5083.8 2221.52  5142.1 2224.02  5231.3 2225.44  5243.6 2226.45  5258.6 2226.68
#Mann=5,-1,0
  4799.4    0.07       0  4983.1    0.16       0  5018.2    0.07       0
  5022.2    0.16       0  5083.8    0.07       0
Bank Sta=5018.2,5022.2
Exp/Cntr=0.3,0.1

Type RM Length L Ch R = 1,7350,81,81,81
BEGIN DESCRIPTION:
Elm 76 7350.2
END DESCRIPTION:
XS GIS Cut Line= 3
      1528631.41      6759889.91      1528831.92      6759875.59
      1529084.55      6759784.44
#Sta/Elev= 30
  4791.2 2226.63  4804.8 2226.02  4824.9 2226.98  4844.9 2224.46  4865.0 2220.89
  4889.1 2220.96  4915.1 2218.18  4945.2 2211.68  4958.7 2202.16  4975.3 2190.56
  4983.3 2190.51  4983.5 2190.01  4987.0 2190.01  4987.3 2190.51  4991.3 2194.42
  5025.7 2196.48  5038.0 2203.94  5049.7 2208.96  5061.7 2216.40  5069.9 2220.01
  5080.5 2221.06  5092.4 2222.08  5117.7 2222.29  5143.1 2221.31  5148.4 2222.42
  5173.8 2222.42  5179.1 2223.22  5218.8 2225.48  5250.6 2225.98  5260.8 2227.33
#Mann=5,-1,0
  4791.2    0.07       0  4958.7    0.16       0  4983.3    0.07       0
  4987.3    0.16       0  5049.7    0.07       0
Bank Sta=4983.3,4987.3
Exp/Cntr=0.3,0.1

Type RM Length L Ch R = 1,7269,68,68,68
BEGIN DESCRIPTION:
Elm 76 7268.91
END DESCRIPTION:
XS GIS Cut Line= 3
      1528747.26      6760024.05      1528897.02      6759930.28
      1529067.59      6759833.93
#Sta/Elev= 30
  4823.8 2220.13  4841.7 2221.71  4847.6 2223.52  4856.5 2223.78  4878.3 2219.81
  4884.2 2217.17  4899.5 2214.72  4905.4 2212.72  4914.8 2211.95  4941.9 2205.94
  4950.9 2203.41  4957.2 2199.32  4963.1 2197.94  4972.6 2193.79  5000.6 2188.53
  5007.6 2188.24  5007.9 2187.74  5011.6 2188.24  5021.1 2195.80  5031.3 2200.96
  5037.0 2209.05  5046.5 2215.05  5052.9 2218.71  5058.7 2219.85  5096.2 2217.27
  5102.0 2218.76  5117.9 2220.13  5124.5 2219.87  5161.2 2222.56  5196.4 2222.50
#Mann=5,-1,0
  4823.8    0.07       0  5000.6    0.16       0  5007.6    0.07       0
  5011.6    0.16       0  5046.5    0.07       0
Bank Sta=5007.6,5011.6
Exp/Cntr=0.3,0.1

Type RM Length L Ch R = 1,7201,107,107,107
BEGIN DESCRIPTION:
Elm 76 7201.444
END DESCRIPTION:
XS GIS Cut Line= 3
      1528755.01      6760187.99      1528944.21      6759978.34
      1529120.78      6759863.55
#Sta/Elev= 30
  4717.6 2246.38  4731.4 2242.74  4753.1 2232.79  4767.3 2227.97  4788.2 2225.37
  4809.9 2220.20  4824.1 2214.15  4830.8 2209.62  4859.2 2204.81  4865.9 2208.87
  4873.4 2206.60  4880.1 2208.99  4887.6 2204.80  4894.3 2203.90  4922.7 2195.01
  4957.8 2192.15  4965.3 2189.84  4972.8 2191.19  4993.7 2187.37  5012.3 2186.66
  5012.6 2186.16  5016.3 2186.66  5029.5 2196.69  5036.7 2206.73  5050.6 2211.59
  5067.9 2214.81  5080.8 2217.48  5123.0 2220.63  5167.9 2218.99  5210.6 2222.62
#Mann=5,-1,0
  4717.6    0.07       0  4957.8    0.16       0  5012.3    0.07       0
  5016.3    0.16       0  5067.9    0.07       0
Bank Sta=5012.3,5016.3
Exp/Cntr=0.3,0.1