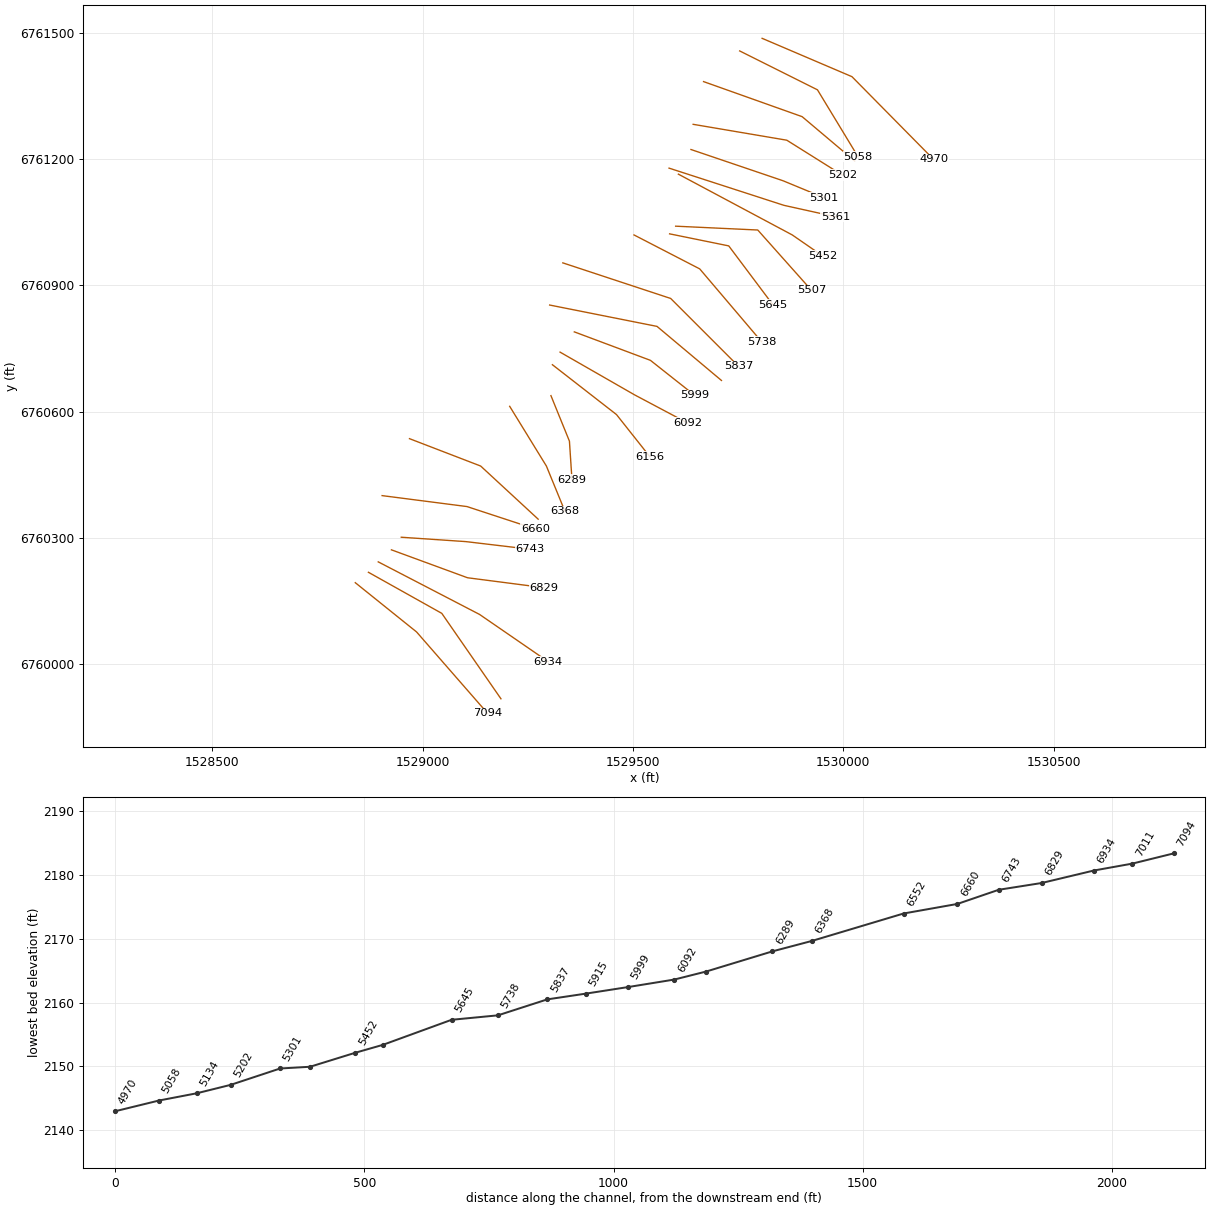
HEC-RAS study Elm 76.prj: Elm 76 Base Level Engineering

--- Elm 76.g01 (geometry) --- (continued)

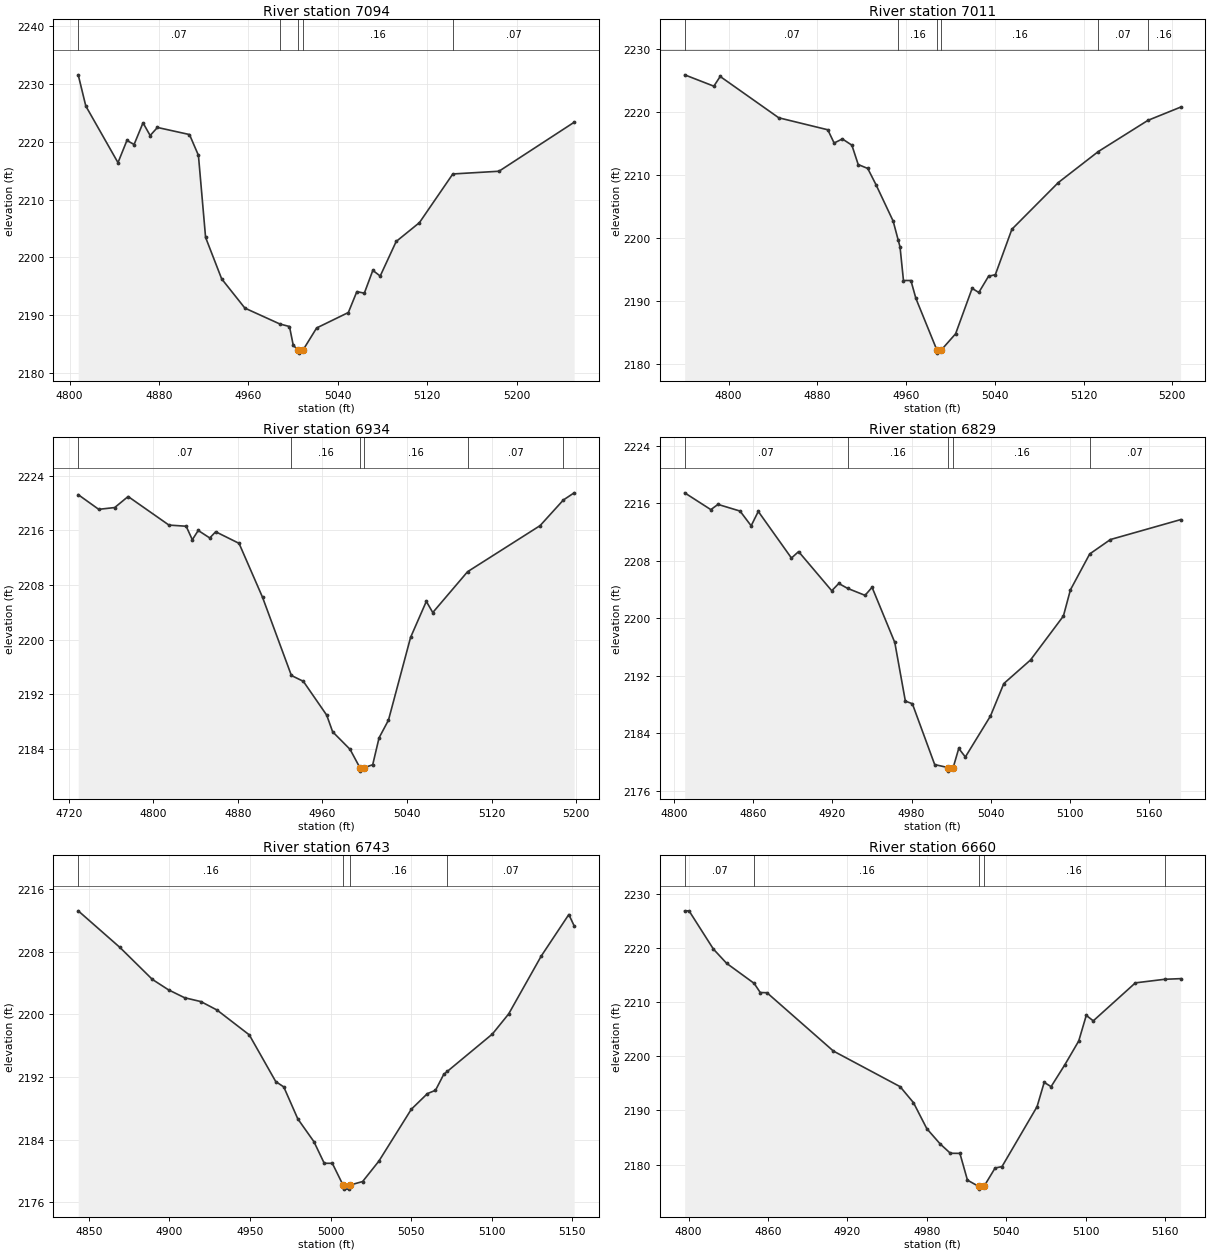
Type RM Length L Ch R = 1,7094,83,83,83
BEGIN DESCRIPTION:
Elm 76 7094.07
END DESCRIPTION:
XS GIS Cut Line= 3
      1528839.77      6760193.27      1528985.56      6760076.11
      1529154.43      6759882.56
#Sta/Elev= 30
  4807.7 2231.61  4814.5 2226.20  4843.3 2216.39  4851.3 2220.24  4857.7 2219.53
  4865.7 2223.29  4872.1 2221.09  4878.6 2222.49  4907.3 2221.26  4915.3 2217.66
  4921.7 2203.44  4936.1 2196.25  4956.9 2191.18  4988.2 2188.43  4996.8 2187.99
  5000.2 2184.72  5004.8 2183.88  5005.1 2183.38  5008.8 2183.88  5021.1 2187.74
  5049.5 2190.42  5057.1 2194.04  5063.8 2193.77  5071.4 2197.72  5078.0 2196.74
  5092.3 2202.73  5113.1 2205.99  5143.0 2214.43  5184.3 2214.90  5251.6 2223.39
#Mann=5,-1,0
  4807.7    0.07       0  4988.2    0.16       0  5004.8    0.07       0
  5008.8    0.16       0  5143.0    0.07       0
Bank Sta=5004.8,5008.8
Exp/Cntr=0.3,0.1

Type RM Length L Ch R = 1,7011,77,77,77
BEGIN DESCRIPTION:
Elm 76 7010.72
END DESCRIPTION:
XS GIS Cut Line= 3
      1528871.02      6760218.02      1529045.46      6760120.38
      1529186.11      6759917.22
#Sta/Elev= 30
  4760.5 2225.89  4786.8 2224.09  4792.5 2225.63  4845.3 2219.08  4889.5 2217.18
  4895.2 2215.08  4902.6 2215.73  4911.2 2214.74  4916.9 2211.67  4925.5 2211.05
  4932.9 2208.49  4948.4 2202.71  4952.9 2199.73  4954.6 2198.61  4957.7 2193.29
  4964.4 2193.29  4968.9 2190.45  4987.8 2182.28  4988.1 2181.78  4991.8 2182.28
  5004.7 2184.85  5019.6 2192.05  5025.6 2191.39  5034.4 2193.97  5040.5 2194.21
  5055.4 2201.41  5097.3 2208.82  5133.3 2213.73  5178.1 2218.68  5207.5 2220.77
#Mann=6,-1,0
  4760.5    0.07       0  4952.9    0.16       0  4987.8    0.07       0
  4991.8    0.16       0  5133.3    0.07       0  5178.1    0.16       0
Bank Sta=4987.8,4991.8
Exp/Cntr=0.3,0.1

Type RM Length L Ch R = 1,6934,105,105,105
BEGIN DESCRIPTION:
Elm 76 6933.5
END DESCRIPTION:
XS GIS Cut Line= 3
      1528894.40      6760242.79      1529135.30      6760117.78
      1529298.09      6760005.78
#Sta/Elev= 30
  4729.0 2221.25  4748.4 2219.10  4763.5 2219.36  4776.2 2220.98  4814.8 2216.79
  4831.1 2216.62  4836.9 2214.64  4842.5 2216.00  4853.4 2214.90  4859.0 2215.81
  4881.1 2214.11  4903.3 2206.20  4930.6 2194.73  4941.9 2193.87  4964.0 2188.91
  4969.6 2186.47  4986.1 2183.89  4995.4 2181.20  4995.7 2180.70  4999.4 2181.20
  5007.5 2181.64  5013.5 2185.58  5022.4 2188.18  5043.3 2200.31  5058.2 2205.60
  5064.3 2203.96  5097.2 2209.95  5165.8 2216.71  5187.8 2220.47  5198.0 2221.52
#Mann=6,-1,0
  4729.0    0.07       0  4930.6    0.16       0  4995.4    0.07       0
  4999.4    0.16       0  5097.2    0.07       0  5187.8    0.16       0
Bank Sta=4995.4,4999.4
Exp/Cntr=0.3,0.1

Type RM Length L Ch R = 1,6829,86,86,86
BEGIN DESCRIPTION:
Elm 76 6828.6
END DESCRIPTION:
XS GIS Cut Line= 3
      1528925.69      6760271.42      1529106.66      6760205.02
      1529287.68      6760181.58
#Sta/Elev= 30
  4808.3 2217.48  4828.1 2215.14  4833.5 2215.87  4850.2 2214.94  4858.6 2212.89
  4864.0 2214.89  4889.1 2208.40  4894.5 2209.30  4919.6 2203.85  4924.9 2204.86
  4931.6 2204.18  4944.8 2203.21  4950.1 2204.33  4967.3 2196.65  4975.3 2188.49
  4980.6 2188.12  4997.5 2179.65  5007.5 2179.24  5007.7 2178.74  5011.5 2179.24
  5015.7 2181.90  5020.7 2180.71  5039.7 2186.41  5049.8 2190.93  5070.0 2194.21
  5094.9 2200.33  5100.2 2203.97  5114.8 2208.97  5130.5 2210.98  5183.6 2213.75
#Mann=5,-1,0
  4808.3    0.07       0  4931.6    0.16       0  5007.5    0.07       0
  5011.5    0.16       0  5114.8    0.07       0
Bank Sta=5007.5,5011.5
Exp/Cntr=0.3,0.1

Type RM Length L Ch R = 1,6743,83,83,83
BEGIN DESCRIPTION:
Elm 76 6743.33
END DESCRIPTION:
XS GIS Cut Line= 3
      1528949.12      6760301.37      1529102.75      6760290.96
      1529255.30      6760272.86
#Sta/Elev= 30
  4843.5 2213.22  4869.4 2208.54  4889.5 2204.46  4899.5 2203.13  4909.5 2202.12
  4919.6 2201.63  4929.6 2200.55  4949.6 2197.38  4966.0 2191.42  4971.0 2190.73
  4979.7 2186.65  4989.7 2183.74  4996.1 2180.98  5001.1 2180.98  5007.8 2178.18
  5008.1 2177.68  5011.6 2177.68  5011.8 2178.18  5019.9 2178.65  5030.0 2181.26
  5050.1 2187.88  5060.1 2189.88  5065.1 2190.30  5070.2 2192.33  5072.4 2192.71
  5100.4 2197.49  5110.5 2200.06  5130.7 2207.45  5147.8 2212.75  5151.1 2211.30
#Mann=4,-1,0
  4843.5    0.16       0  5007.8    0.07       0  5011.8    0.16       0
  5072.4    0.07       0
Bank Sta=5007.8,5011.8
Exp/Cntr=0.3,0.1

Type RM Length L Ch R = 1,6660,108,108,108
BEGIN DESCRIPTION:
Elm 76 6659.63
END DESCRIPTION:
XS GIS Cut Line= 3
      1528903.52      6760400.33      1529105.35      6760374.29
      1529268.12      6760320.90
#Sta/Elev= 30
  4797.0 2226.84  4800.3 2226.84  4818.7 2219.78  4828.7 2217.15  4849.5 2213.45
  4854.1 2211.76  4859.2 2211.72  4909.4 2200.95  4959.8 2194.38  4969.9 2191.43
  4980.0 2186.62  4990.1 2183.80  4997.8 2182.08  5005.0 2182.06  5010.7 2177.12
  5019.2 2175.96  5019.4 2175.46  5023.2 2175.96  5031.6 2179.36  5036.8 2179.62
  5063.3 2190.68  5068.7 2195.17  5073.9 2194.38  5084.3 2198.42  5094.8 2202.81
  5100.5 2207.54  5105.8 2206.53  5137.6 2213.54  5159.7 2214.20  5171.8 2214.32
#Mann=5,-1,0
  4797.0    0.07       0  4849.5    0.16       0  5019.2    0.07       0
  5023.2    0.16       0  5159.7    0.07       0
Bank Sta=5019.2,5023.2
Exp/Cntr=0.3,0.1

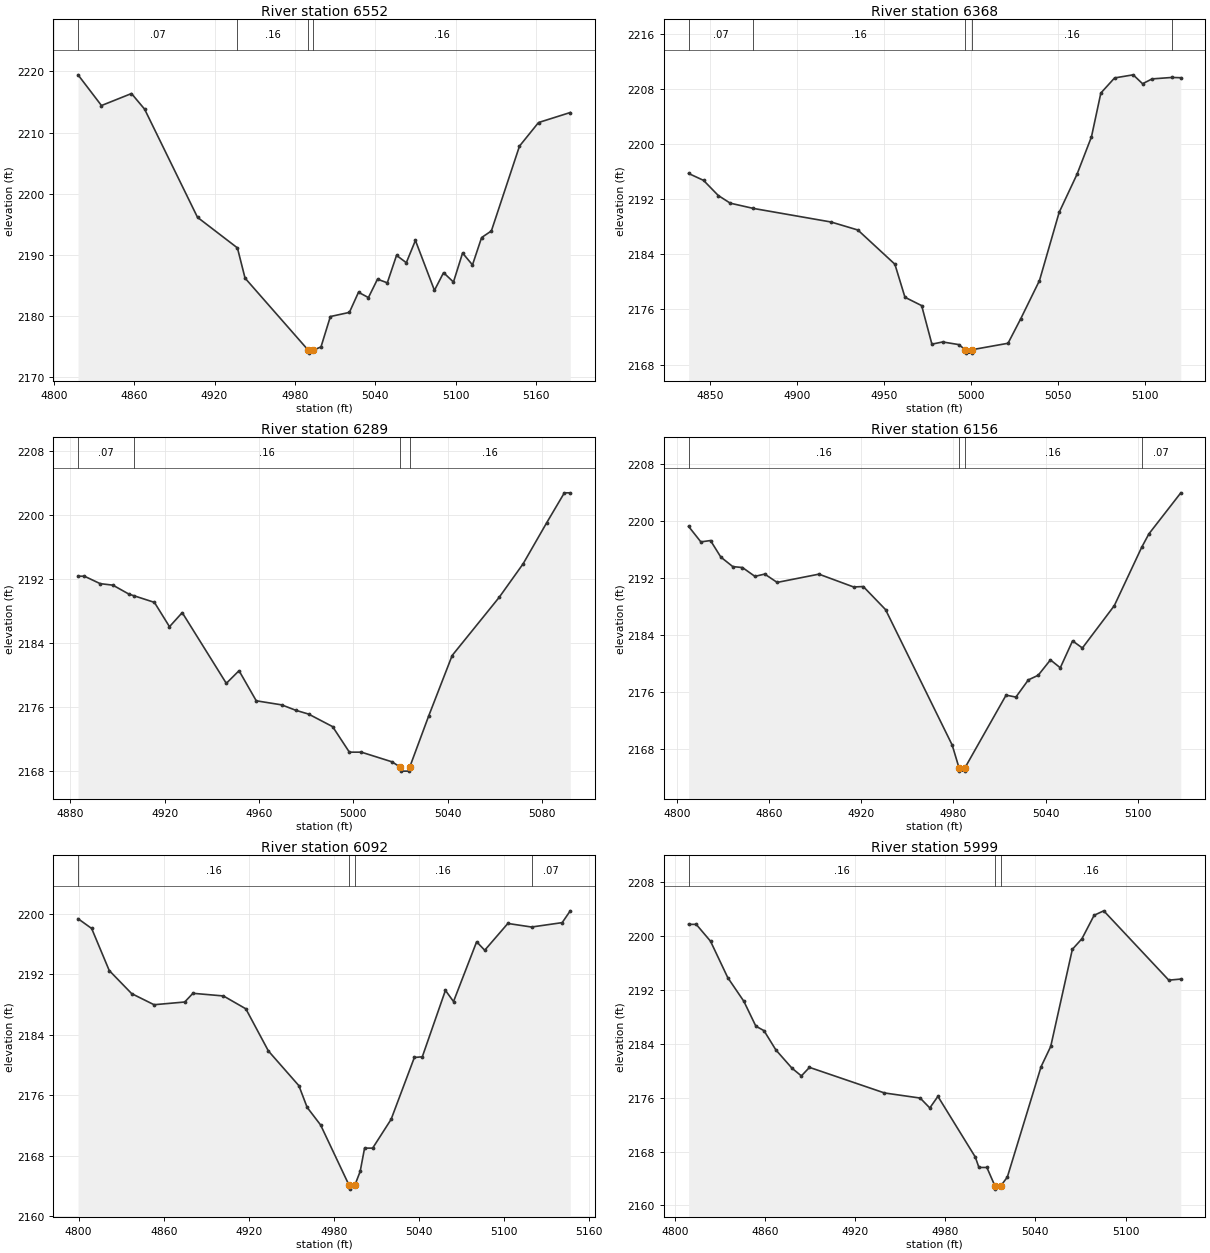
Type RM Length L Ch R = 1,6552,184,184,184
BEGIN DESCRIPTION:
Elm 76 6551.72
END DESCRIPTION:
XS GIS Cut Line= 3
      1528968.63      6760535.75      1529137.91      6760470.64
      1529274.63      6760344.33
#Sta/Elev= 30
  4818.1 2219.45  4835.6 2214.43  4858.0 2216.39  4867.8 2213.84  4907.3 2196.16
  4937.1 2191.16  4942.8 2186.22  4989.9 2174.46  4990.2 2173.96  4993.9 2174.46
  4999.5 2174.98  5006.5 2179.94  5020.7 2180.62  5027.5 2183.91  5034.9 2183.04
  5041.7 2186.05  5049.0 2185.45  5055.9 2189.94  5063.2 2188.74  5070.0 2192.38
  5084.2 2184.22  5091.0 2187.11  5098.4 2185.58  5105.2 2190.32  5112.6 2188.38
  5119.4 2192.85  5126.7 2193.93  5147.7 2207.80  5161.9 2211.65  5185.6 2213.29
#Mann=4,-1,0
  4818.1    0.07       0  4937.1    0.16       0  4989.9    0.07       0
  4993.9    0.16       0
Bank Sta=4989.9,4993.9
Exp/Cntr=0.3,0.1

Type RM Length L Ch R = 1,6368,79,79,79
BEGIN DESCRIPTION:
Elm 76 6368.35
END DESCRIPTION:
XS GIS Cut Line= 3
      1529206.92      6760612.57      1529294.16      6760470.64
      1529338.36      6760362.74
#Sta/Elev= 30
  4837.4 2195.71  4846.0 2194.71  4854.5 2192.51  4861.4 2191.40  4874.7 2190.64
  4919.4 2188.67  4934.8 2187.51  4956.1 2182.55  4961.9 2177.76  4971.5 2176.55
  4977.4 2170.96  4983.6 2171.28  4992.8 2170.90  4996.6 2170.16  4996.9 2169.66
  5000.4 2169.66  5000.6 2170.16  5021.2 2171.09  5028.5 2174.64  5039.3 2180.19
  5050.6 2190.06  5060.9 2195.60  5069.2 2201.02  5074.6 2207.37  5082.5 2209.56
  5093.2 2210.01  5098.6 2208.72  5104.1 2209.42  5115.5 2209.63  5120.6 2209.59
#Mann=5,-1,0
  4837.4    0.07       0  4874.7    0.16       0  4996.6    0.07       0
  5000.6    0.16       0  5115.5    0.07       0
Bank Sta=4996.6,5000.6
Exp/Cntr=0.3,0.1

Type RM Length L Ch R = 1,6289,133,133,133
BEGIN DESCRIPTION:
Elm 76 6288.688
END DESCRIPTION:
XS GIS Cut Line= 3
      1529304.99      6760638.01      1529348.95      6760529.80
      1529355.00      6760438.00
#Sta/Elev= 30
  4883.2 2192.39  4885.9 2192.39  4892.6 2191.46  4898.0 2191.27  4904.8 2190.15
  4907.0 2189.94  4915.6 2189.12  4922.0 2186.08  4927.4 2187.84  4946.1 2179.00
  4951.5 2180.58  4958.8 2176.82  4969.6 2176.31  4975.6 2175.63  4981.0 2175.16
  4991.2 2173.59  4998.3 2170.40  5003.4 2170.40  5016.4 2169.19  5019.9 2168.53
  5020.1 2168.03  5023.6 2168.03  5023.9 2168.53  5031.9 2174.89  5041.9 2182.48
  5061.9 2189.77  5072.0 2193.94  5082.0 2199.07  5089.5 2202.81  5092.0 2202.81
#Mann=4,-1,0
  4883.2    0.07       0  4907.0    0.16       0  5019.9    0.07       0
  5023.9    0.16       0
Bank Sta=5019.9,5023.9
Exp/Cntr=0.3,0.1

Type RM Length L Ch R = 1,6156,64,64,64
BEGIN DESCRIPTION:
Elm 76 6155.54
END DESCRIPTION:
XS GIS Cut Line= 3
      1529308.44      6760711.56      1529460.82      6760593.04
      1529540.03      6760493.06
#Sta/Elev= 30
  4807.5 2199.24  4815.5 2197.06  4821.8 2197.25  4828.5 2194.93  4836.3 2193.59
  4842.6 2193.46  4850.7 2192.22  4857.1 2192.54  4865.2 2191.37  4892.4 2192.53
  4915.0 2190.73  4921.3 2190.79  4935.8 2187.55  4979.2 2168.53  4983.6 2165.37
  4983.8 2164.87  4987.3 2164.87  4987.6 2165.37  5014.3 2175.54  5020.7 2175.27
  5028.8 2177.68  5035.2 2178.33  5043.2 2180.49  5049.6 2179.38  5057.6 2183.16
  5064.0 2182.16  5084.8 2188.11  5102.6 2196.29  5107.3 2198.18  5128.1 2203.95
#Mann=4,-1,0
  4807.5    0.16       0  4983.6    0.07       0  4987.6    0.16       0
  5102.6    0.07       0
Bank Sta=4983.6,4987.6
Exp/Cntr=0.3,0.1

Type RM Length L Ch R = 1,6092,93,93,93
BEGIN DESCRIPTION:
Elm 76 6091.79
END DESCRIPTION:
XS GIS Cut Line= 3
      1529326.68      6760741.49      1529503.79      6760639.92
      1529629.96      6760572.97
#Sta/Elev= 30
  4799.6 2199.35  4809.2 2198.06  4821.6 2192.50  4837.4 2189.45  4853.2 2187.98
  4874.8 2188.34  4880.6 2189.49  4902.1 2189.14  4917.9 2187.44  4933.8 2181.87
  4955.3 2177.28  4961.1 2174.42  4970.6 2172.09  4990.7 2164.11  4991.0 2163.61
  4994.7 2164.11  4998.5 2165.95  5001.6 2169.03  5007.3 2169.03  5020.3 2172.83
  5036.7 2181.01  5042.3 2181.10  5058.6 2189.88  5064.3 2188.40  5080.6 2196.30
  5086.3 2195.18  5102.6 2198.72  5119.3 2198.25  5140.9 2198.83  5146.6 2200.39
#Mann=4,-1,0
  4799.6    0.16       0  4990.7    0.07       0  4994.7    0.16       0
  5119.3    0.07       0
Bank Sta=4990.7,4994.7
Exp/Cntr=0.3,0.1

Type RM Length L Ch R = 1,5999,84,84,84
BEGIN DESCRIPTION:
Elm 76 5999.16
END DESCRIPTION:
XS GIS Cut Line= 3
      1529360.54      6760789.66      1529541.55      6760721.95
      1529647.04      6760638.60
#Sta/Elev= 30
  4809.1 2201.77  4814.2 2201.77  4823.7 2199.27  4835.2 2193.85  4845.9 2190.34
  4853.9 2186.64  4859.3 2185.98  4867.2 2183.12  4877.9 2180.41  4884.2 2179.25
  4889.6 2180.52  4939.5 2176.72  4963.3 2175.96  4969.7 2174.49  4975.1 2176.21
  5000.0 2167.19  5002.4 2165.65  5007.7 2165.65  5013.0 2162.93  5013.2 2162.43
  5017.0 2162.93  5021.3 2164.21  5043.8 2180.63  5050.2 2183.63  5064.6 2198.06
  5071.0 2199.64  5079.1 2203.12  5085.5 2203.78  5128.8 2193.48  5136.8 2193.64
#Mann=3,-1,0
  4809.1    0.16       0  5013.0    0.07       0  5017.0    0.16       0
Bank Sta=5013,5017
Exp/Cntr=0.3,0.1

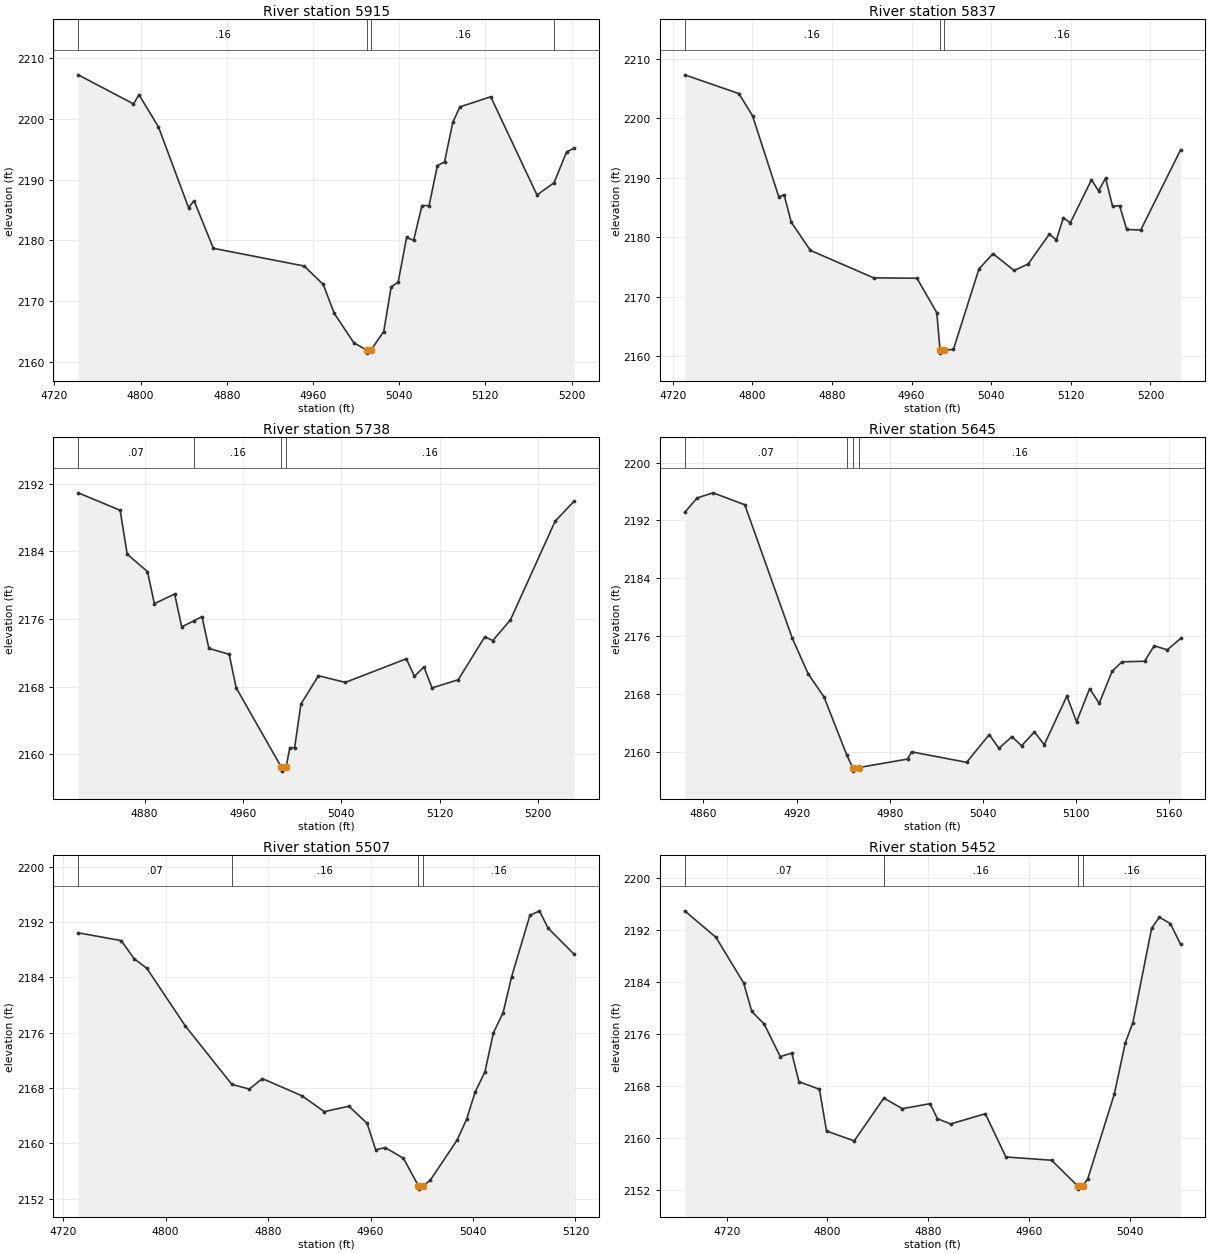
Type RM Length L Ch R = 1,5915,78,78,78
BEGIN DESCRIPTION:
Elm 76 5914.78
END DESCRIPTION:
XS GIS Cut Line= 3
      1529301.97      6760853.46      1529557.18      6760802.68
      1529710.38      6760674.14
#Sta/Elev= 30
  4742.2 2207.26  4793.5 2202.47  4798.6 2203.98  4816.7 2198.67  4844.6 2185.38
  4849.7 2186.52  4867.6 2178.68  4951.9 2175.76  4969.6 2172.72  4979.8 2167.96
  4997.9 2163.13  5009.8 2161.91  5010.0 2161.41  5013.8 2161.91  5025.7 2164.97
  5032.6 2172.33  5039.1 2173.10  5046.9 2180.46  5053.4 2179.99  5061.2 2185.72
  5067.8 2185.72  5075.5 2192.32  5082.1 2192.89  5089.8 2199.45  5096.4 2201.98
  5125.0 2203.65  5167.9 2187.47  5183.7 2189.48  5195.4 2194.55  5202.4 2195.19
#Mann=4,-1,0
  4742.2    0.16       0  5009.8    0.07       0  5013.8    0.16       0
  5183.7    0.07       0
Bank Sta=5009.8,5013.8
Exp/Cntr=0.3,0.1

Type RM Length L Ch R = 1,5837,99,99,99
BEGIN DESCRIPTION:
Elm 76 5836.79
END DESCRIPTION:
XS GIS Cut Line= 3
      1529333.25      6760953.71      1529589.73      6760869.08
      1529751.25      6760707.56
#Sta/Elev= 30
  4731.9 2207.26  4786.4 2204.11  4800.1 2200.38  4826.6 2186.72  4831.8 2187.13
  4839.0 2182.50  4858.3 2177.76  4921.8 2173.15  4965.4 2173.08  4985.3 2167.30
  4988.6 2161.00  4988.8 2160.50  4992.6 2161.00  5002.0 2161.12  5027.7 2174.65
  5041.8 2177.21  5063.0 2174.39  5077.2 2175.48  5098.4 2180.49  5105.5 2179.53
  5112.5 2183.22  5119.6 2182.42  5140.8 2189.63  5147.9 2187.77  5155.0 2189.92
  5162.0 2185.16  5169.1 2185.27  5176.2 2181.28  5190.3 2181.18  5230.4 2194.67
#Mann=3,-1,0
  4731.9    0.16       0  4988.6    0.07       0  4992.6    0.16       0
Bank Sta=4988.6,4992.6
Exp/Cntr=0.3,0.1

Type RM Length L Ch R = 1,5738,93,93,93
BEGIN DESCRIPTION:
Elm 76 5737.99
END DESCRIPTION:
XS GIS Cut Line= 3
      1529502.48      6761020.13      1529658.74      6760939.39
      1529805.86      6760766.23
#Sta/Elev= 30
  4826.1 2190.94  4860.2 2188.87  4865.9 2183.68  4882.4 2181.62  4888.0 2177.82
  4904.5 2178.96  4910.2 2175.08  4919.9 2175.77  4926.7 2176.29  4932.3 2172.53
  4948.8 2171.83  4954.5 2167.86  4991.1 2158.50  4991.4 2158.00  4995.1 2158.50
  4998.1 2160.77  5002.0 2160.77  5007.1 2165.93  5021.4 2169.29  5043.2 2168.50
  5092.8 2171.30  5099.4 2169.23  5107.1 2170.33  5113.7 2167.85  5135.0 2168.82
  5156.5 2173.89  5163.1 2173.46  5177.4 2175.90  5213.7 2187.57  5229.2 2189.96
#Mann=4,-1,0
  4826.1    0.07       0  4919.9    0.16       0  4991.1    0.07       0
  4995.1    0.16       0
Bank Sta=4991.1,4995.1
Exp/Cntr=0.3,0.1

Type RM Length L Ch R = 1,5645,138,138,138
BEGIN DESCRIPTION:
Elm 76 5644.8
END DESCRIPTION:
XS GIS Cut Line= 3
      1529587.12      6761022.73      1529727.75      6760994.08
      1529833.22      6760853.46
#Sta/Elev= 30
  4847.9 2193.11  4855.9 2195.11  4866.2 2195.82  4886.6 2194.17  4917.2 2175.69
  4927.4 2170.77  4937.6 2167.57  4952.3 2159.51  4956.0 2157.80  4956.2 2157.30
  4960.0 2157.80  4991.4 2158.97  4994.0 2159.97  5029.4 2158.52  5044.0 2162.36
  5050.2 2160.46  5058.6 2162.08  5064.8 2160.81  5073.1 2162.72  5079.4 2160.96
  5094.0 2167.70  5100.2 2164.13  5108.6 2168.71  5114.8 2166.69  5123.1 2171.13
  5129.4 2172.43  5144.0 2172.51  5150.2 2174.65  5158.6 2174.09  5167.2 2175.66
#Mann=4,-1,0
  4847.9    0.07       0  4952.3    0.16       0  4956.0    0.07       0
  4960.0    0.16       0
Bank Sta=4956,4960
Exp/Cntr=0.3,0.1

Type RM Length L Ch R = 1,5507,55,55,55
BEGIN DESCRIPTION:
Elm 76 5506.87
END DESCRIPTION:
XS GIS Cut Line= 3
      1529601.48      6761040.96      1529796.76      6761031.84
      1529924.35      6760888.63
#Sta/Elev= 30
  4731.7 2190.46  4765.3 2189.33  4775.3 2186.73  4785.3 2185.32  4815.3 2176.99
  4851.7 2168.52  4865.4 2167.85  4875.4 2169.37  4906.4 2166.88  4923.8 2164.59
  4943.1 2165.36  4957.3 2162.90  4964.0 2159.06  4971.5 2159.38  4985.7 2157.83
  4997.3 2153.87  4997.6 2153.37  5001.3 2153.87  5006.6 2154.65  5027.5 2160.44
  5035.0 2163.47  5041.7 2167.43  5049.3 2170.32  5055.9 2175.97  5063.5 2178.90
  5070.2 2184.12  5084.4 2192.97  5091.9 2193.64  5098.6 2191.15  5119.0 2187.36
#Mann=4,-1,0
  4731.7    0.07       0  4851.7    0.16       0  4997.3    0.07       0
  5001.3    0.16       0
Bank Sta=4997.3,5001.3
Exp/Cntr=0.3,0.1

Type RM Length L Ch R = 1,5452,91,91,91
BEGIN DESCRIPTION:
Elm 76 5451.82
END DESCRIPTION:
XS GIS Cut Line= 3
      1529608.00      6761164.63      1529878.79      6761020.12
      1529950.17      6760970.81
#Sta/Elev= 30
  4686.7 2195.00  4711.5 2190.93  4733.5 2183.89  4740.0 2179.50  4749.8 2177.57
  4762.6 2172.54  4771.7 2173.10  4777.4 2168.69  4793.7 2167.52  4799.3 2161.09
  4821.3 2159.57  4844.8 2166.16  4859.5 2164.53  4881.5 2165.30  4887.3 2163.00
  4897.8 2162.18  4925.4 2163.75  4941.7 2157.09  4978.0 2156.59  4998.6 2152.64
  4998.9 2152.14  5002.6 2152.64  5006.7 2153.73  5027.7 2166.74  5036.5 2174.68
  5042.5 2177.77  5057.4 2192.32  5063.5 2194.03  5072.3 2193.03  5080.4 2189.83
#Mann=4,-1,0
  4686.7    0.07       0  4844.8    0.16       0  4998.6    0.07       0
  5002.6    0.16       0
Bank Sta=4998.6,5002.6
Exp/Cntr=0.3,0.1

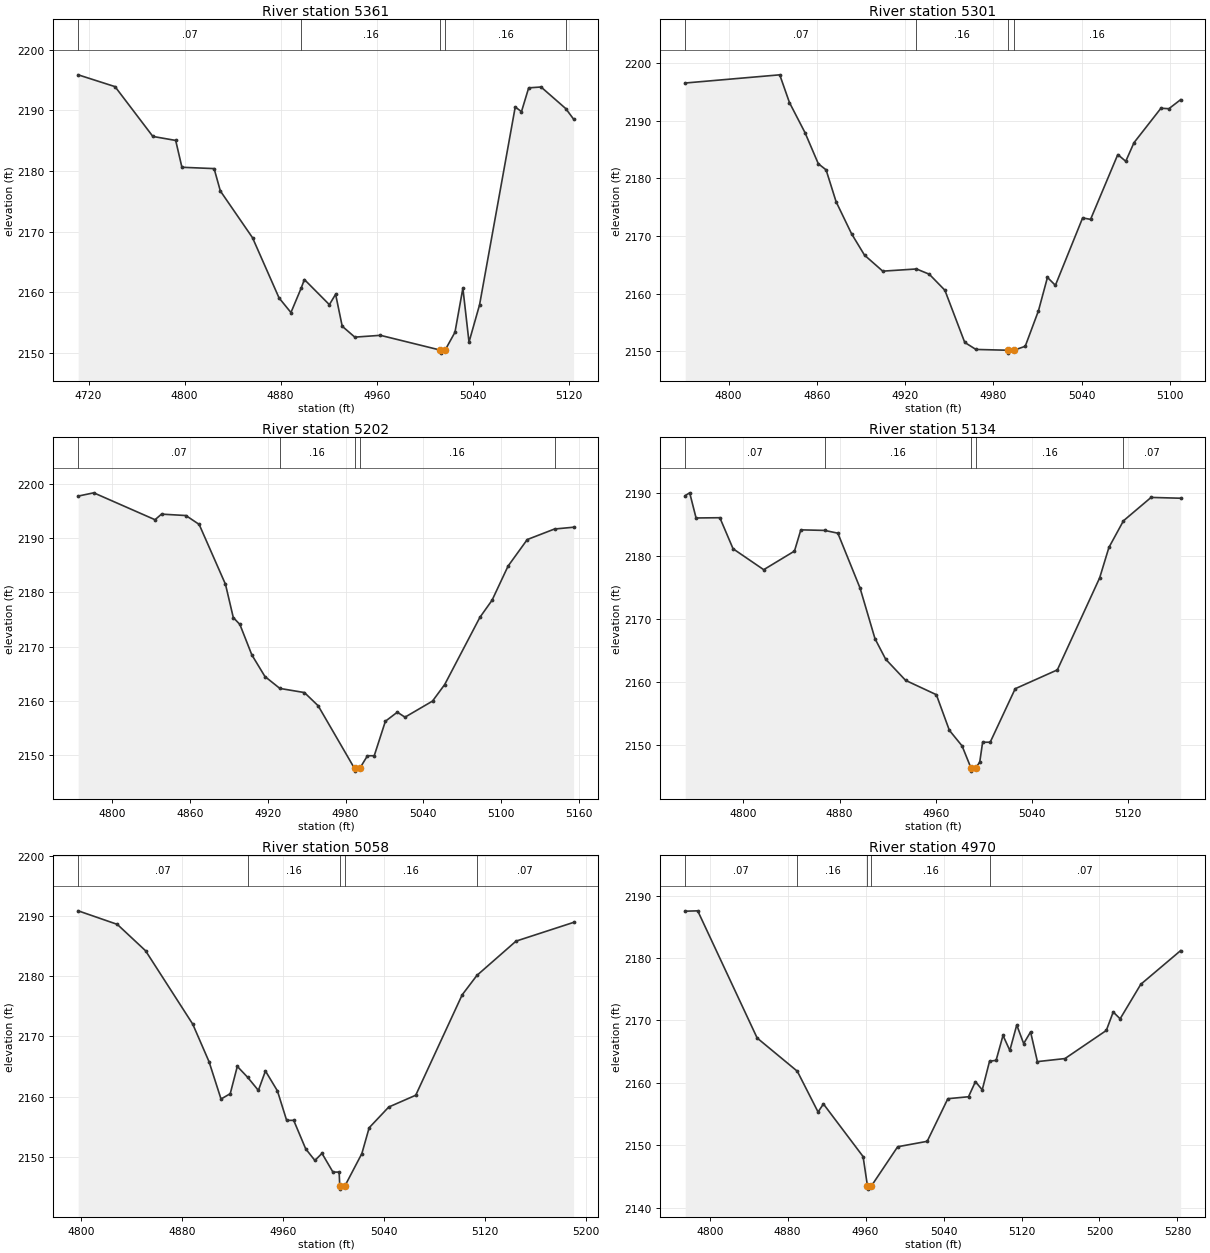
Type RM Length L Ch R = 1,5361,60,60,60
BEGIN DESCRIPTION:
Elm 76 5361.15
END DESCRIPTION:
XS GIS Cut Line= 3
      1529585.81      6761178.98      1529859.26      6761090.44
      1529981.48      6761063.42
#Sta/Elev= 30
  4711.4 2195.88  4742.1 2193.93  4773.6 2185.71  4792.6 2185.05  4797.8 2180.62
  4824.6 2180.40  4829.8 2176.71  4856.6 2168.99  4878.7 2159.05  4888.6 2156.64
  4897.1 2160.66  4899.8 2162.09  4920.6 2157.94  4925.8 2159.66  4931.3 2154.38
  4941.8 2152.58  4963.1 2152.88  5013.0 2150.44  5013.2 2149.94  5017.0 2150.44
  5025.2 2153.38  5031.8 2160.66  5036.9 2151.76  5045.7 2157.92  5075.4 2190.57
  5080.6 2189.80  5086.6 2193.73  5096.9 2193.87  5117.4 2190.32  5124.0 2188.57
#Mann=5,-1,0
  4711.4    0.07       0  4897.1    0.16       0  5013.0    0.07       0
  5017.0    0.16       0  5117.4    0.07       0
Bank Sta=5013,5017
Exp/Cntr=0.3,0.1

Type RM Length L Ch R = 1,5301,99,99,99
BEGIN DESCRIPTION:
Elm 76 5300.96
END DESCRIPTION:
XS GIS Cut Line= 3
      1529637.95      6761223.23      1529856.66      6761149.03
      1529954.29      6761108.67
#Sta/Elev= 30
  4770.6 2196.56  4834.8 2197.98  4841.4 2193.17  4852.0 2187.93  4861.0 2182.55
  4866.3 2181.48  4873.1 2175.95  4883.6 2170.39  4892.4 2166.68  4904.8 2163.90
  4927.7 2164.28  4936.4 2163.37  4947.0 2160.59  4960.5 2151.53  4968.1 2150.31
  4989.9 2150.17  4990.1 2149.67  4993.9 2150.17  5001.6 2150.86  5010.6 2157.03
  5016.7 2162.81  5022.1 2161.44  5040.6 2173.14  5046.0 2172.89  5064.5 2184.14
  5069.9 2182.97  5075.5 2186.20  5093.8 2192.18  5099.2 2192.10  5107.2 2193.67
#Mann=4,-1,0
  4770.6    0.07       0  4927.7    0.16       0  4989.9    0.07       0
  4993.9    0.16       0
Bank Sta=4989.9,4993.9
Exp/Cntr=0.3,0.1

Type RM Length L Ch R = 1,5202,68,68,68
BEGIN DESCRIPTION:
Elm 76 5202.35
END DESCRIPTION:
XS GIS Cut Line= 3
      1529643.13      6761283.14      1529865.77      6761245.38
      1529997.81      6761162.54
#Sta/Elev= 30
  4774.0 2197.73  4786.0 2198.33  4833.2 2193.38  4838.2 2194.41  4857.0 2194.15
  4867.2 2192.52  4887.5 2181.49  4893.5 2175.38  4898.6 2174.10  4907.8 2168.50
  4917.9 2164.52  4929.4 2162.33  4948.3 2161.57  4958.9 2159.14  4986.9 2147.61
  4987.1 2147.11  4990.9 2147.61  4996.9 2149.94  5002.1 2149.94  5010.7 2156.29
  5019.9 2157.96  5025.8 2157.04  5047.0 2160.00  5056.4 2163.05  5083.5 2175.41
  5092.9 2178.57  5105.2 2184.84  5120.0 2189.73  5141.0 2191.67  5155.7 2192.00
#Mann=5,-1,0
  4774.0    0.07       0  4929.4    0.16       0  4986.9    0.07       0
  4990.9    0.16       0  5141.0    0.07       0
Bank Sta=4986.9,4990.9
Exp/Cntr=0.3,0.1

Type RM Length L Ch R = 1,5134,76,76,76
BEGIN DESCRIPTION:
Elm 76 5134.18
END DESCRIPTION:
XS GIS Cut Line= 3
      1529667.88      6761384.70      1529902.23      6761301.37
      1530027.25      6761195.88
#Sta/Elev= 30
  4751.6 2189.63  4755.3 2190.07  4760.6 2186.07  4780.4 2186.11  4791.4 2181.17
  4816.9 2177.84  4842.5 2180.80  4847.8 2184.18  4867.6 2184.09  4878.6 2183.65
  4897.1 2174.91  4909.5 2166.87  4918.4 2163.60  4935.0 2160.23  4960.6 2157.95
  4971.4 2152.29  4982.0 2149.80  4989.4 2146.29  4989.6 2145.79  4993.4 2146.29
  4996.7 2147.24  4999.1 2150.39  5005.4 2150.39  5026.2 2158.90  5061.3 2161.90
  5096.5 2176.54  5104.2 2181.38  5116.3 2185.62  5139.3 2189.34  5163.9 2189.21
#Mann=5,-1,0
  4751.6    0.07       0  4867.6    0.16       0  4989.4    0.07       0
  4993.4    0.16       0  5116.3    0.07       0
Bank Sta=4989.4,4993.4
Exp/Cntr=0.3,0.1

Type RM Length L Ch R = 1,5058,88,88,88
BEGIN DESCRIPTION:
Elm 76 5058.12
END DESCRIPTION:
XS GIS Cut Line= 3
      1529753.75      6761457.64      1529938.69      6761365.18
      1530035.07      6761206.28
#Sta/Elev= 30
  4797.7 2190.86  4828.7 2188.61  4851.1 2184.23  4888.5 2172.04  4901.4 2165.81
  4910.9 2159.61  4918.2 2160.50  4923.8 2165.03  4932.0 2163.22  4940.5 2161.04
  4946.1 2164.27  4955.6 2160.96  4962.9 2156.07  4968.5 2156.07  4978.0 2151.34
  4985.3 2149.41  4990.9 2150.59  4999.6 2147.48  5004.5 2147.48  5005.0 2145.15
  5005.2 2144.65  5009.0 2145.15  5022.5 2150.55  5028.3 2154.84  5043.8 2158.28
  5065.2 2160.24  5102.0 2176.91  5113.7 2180.14  5144.7 2185.83  5190.3 2188.94
#Mann=5,-1,0
  4797.7    0.07       0  4932.0    0.16       0  5005.0    0.07       0
  5009.0    0.16       0  5113.7    0.07       0
Bank Sta=5005,5009
Exp/Cntr=0.3,0.1

Type RM Length L Ch R = 1,4970,72,72,72
BEGIN DESCRIPTION:
Elm 76 4969.85
END DESCRIPTION:
XS GIS Cut Line= 3
      1529807.13      6761487.59      1530020.72      6761396.43
      1530214.70      6761199.84
#Sta/Elev= 30
  4774.9 2187.50  4787.7 2187.56  4848.7 2167.18  4889.9 2161.86  4911.2 2155.33
  4916.7 2156.62  4957.4 2148.19  4961.9 2143.47  4962.1 2142.97  4965.9 2143.47
  4992.9 2149.76  5023.2 2150.63  5044.4 2157.46  5065.6 2157.77  5072.7 2160.19
  5079.7 2158.88  5087.2 2163.47  5093.9 2163.60  5101.0 2167.59  5108.0 2165.19
  5115.1 2169.27  5122.2 2166.29  5129.3 2168.16  5136.3 2163.40  5164.6 2163.89
  5207.0 2168.39  5214.1 2171.35  5221.2 2170.26  5242.4 2175.79  5283.3 2181.19
#Mann=5,-1,0
  4774.9    0.07       0  4889.9    0.16       0  4961.9    0.07       0
  4965.9    0.16       0  5087.2    0.07       0
Bank Sta=4961.9,4965.9
Exp/Cntr=0.3,0.1