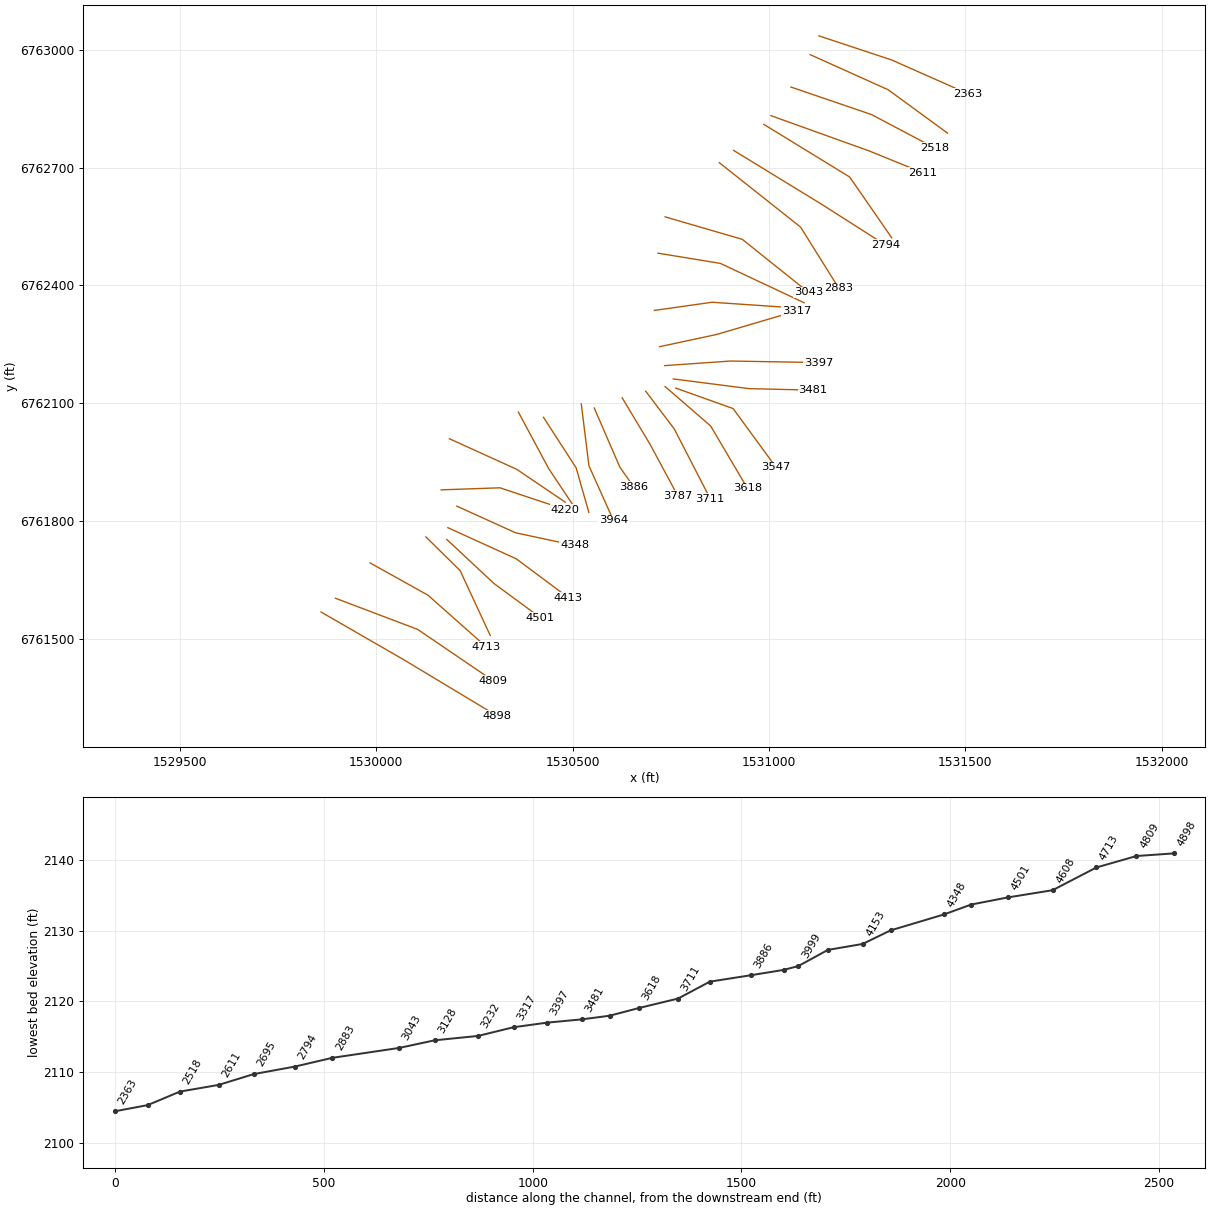
HEC-RAS study Elm 76.prj: Elm 76 Base Level Engineering

--- Elm 76.g01 (geometry) --- (continued)

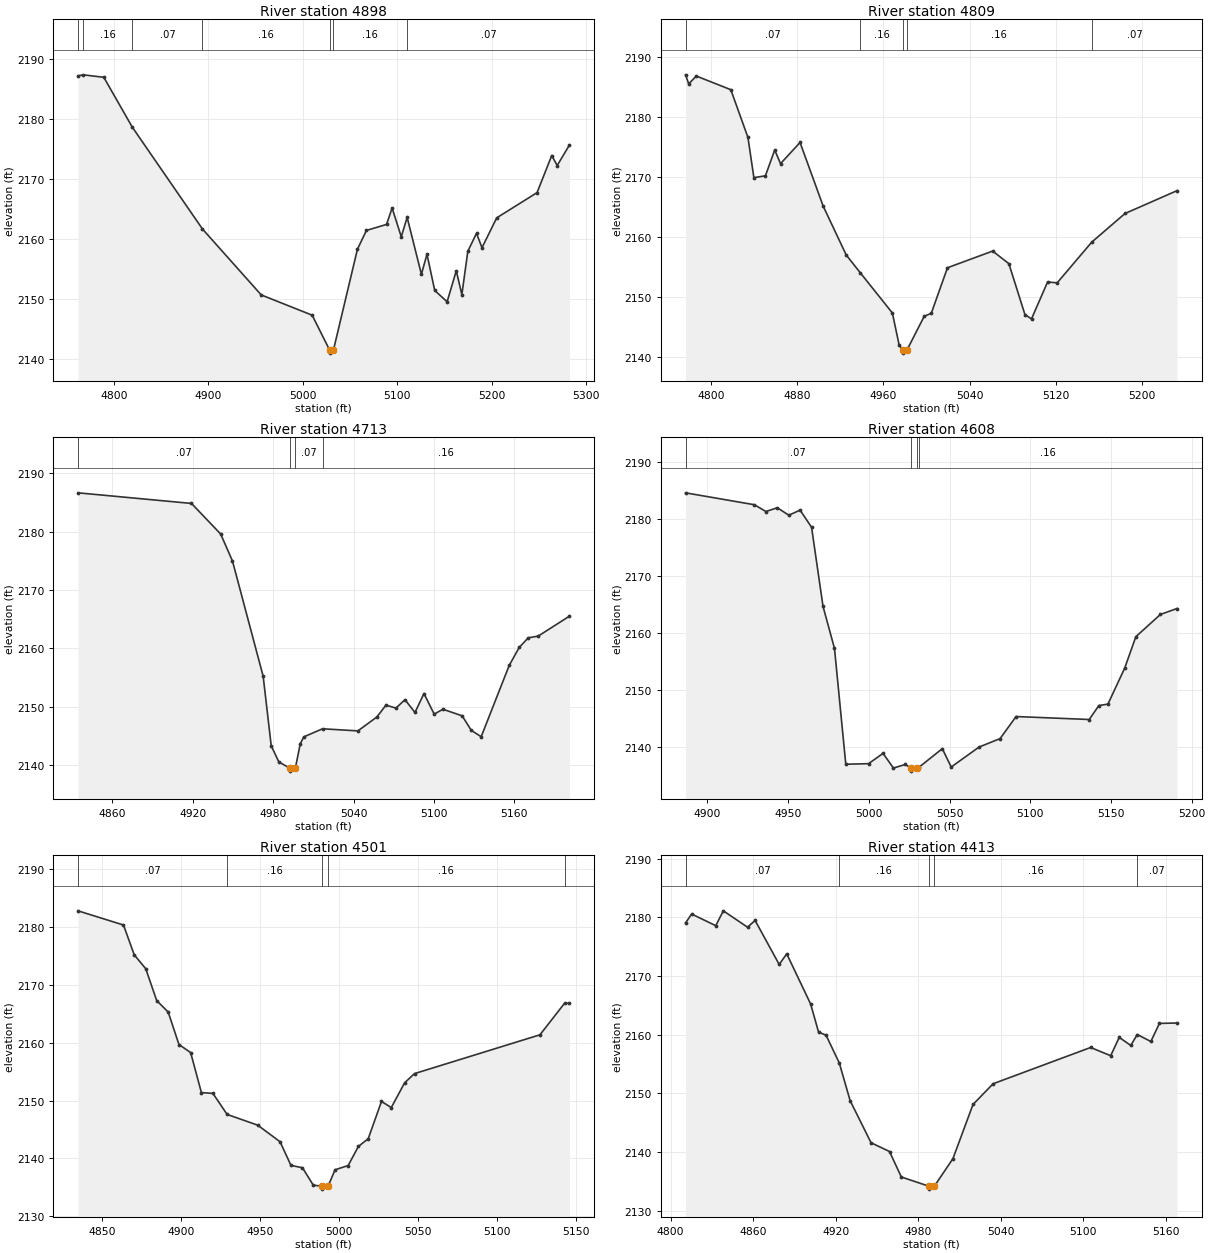
Type RM Length L Ch R = 1,4898,89,89,89
BEGIN DESCRIPTION:
Elm 76 4898.16
END DESCRIPTION:
XS GIS Cut Line= 3
      1529859.29      6761568.28      1530071.50      6761445.90
      1530307.19      6761303.97
#Sta/Elev= 30
  4762.2 2187.20  4767.6 2187.37  4789.5 2186.96  4819.7 2178.63  4893.9 2161.65
  4956.1 2150.65  5010.0 2147.27  5028.5 2141.44  5028.7 2140.94  5032.5 2141.44
  5057.9 2158.27  5067.4 2161.41  5088.7 2162.41  5094.6 2165.14  5104.3 2160.35
  5110.5 2163.59  5125.6 2154.09  5131.5 2157.44  5139.7 2151.39  5152.8 2149.51
  5162.5 2154.68  5168.4 2150.69  5174.7 2157.93  5183.9 2160.93  5189.7 2158.53
  5205.3 2163.51  5248.0 2167.72  5263.5 2173.91  5269.3 2172.24  5282.3 2175.68
#Mann=7,-1,0
  4762.2    0.07       0  4767.6    0.16       0  4819.7    0.07       0
  4893.9    0.16       0  5028.5    0.07       0  5032.5    0.16       0
  5110.5    0.07       0
Bank Sta=5028.5,5032.5
Exp/Cntr=0.3,0.1

Type RM Length L Ch R = 1,4809,96,96,96
BEGIN DESCRIPTION:
Elm 76 4808.84
END DESCRIPTION:
XS GIS Cut Line= 3
      1529895.69      6761603.47      1530105.35      6761524.03
      1530296.75      6761393.82
#Sta/Elev= 30
  4776.5 2187.01  4779.5 2185.50  4786.5 2186.81  4818.5 2184.53  4834.4 2176.56
  4839.9 2169.85  4850.6 2170.16  4859.2 2174.47  4864.6 2172.19  4882.7 2175.72
  4904.1 2165.12  4925.5 2156.95  4938.5 2153.99  4968.3 2147.27  4974.5 2141.98
  4977.8 2141.07  4978.1 2140.57  4981.8 2141.07  4997.8 2146.71  5004.4 2147.23
  5019.4 2154.82  5061.3 2157.60  5076.3 2155.50  5091.2 2147.01  5097.3 2146.28
  5112.2 2152.44  5121.1 2152.30  5153.2 2159.10  5184.0 2163.87  5232.2 2167.68
#Mann=5,-1,0
  4776.5    0.07       0  4938.5    0.16       0  4977.8    0.07       0
  4981.8    0.16       0  5153.2    0.07       0
Bank Sta=4977.8,4981.8
Exp/Cntr=0.3,0.1

Type RM Length L Ch R = 1,4713,105,105,105
BEGIN DESCRIPTION:
Elm 76 4713.11
END DESCRIPTION:
XS GIS Cut Line= 3
      1529984.26      6761693.30      1530131.40      6761611.27
      1530279.85      6761479.74
#Sta/Elev= 30
  4834.3 2186.67  4919.0 2184.85  4940.8 2179.60  4949.6 2174.97  4972.5 2155.21
  4978.5 2143.30  4984.2 2140.52  4992.5 2139.45  4992.7 2138.95  4996.5 2139.45
  5000.2 2143.65  5002.8 2144.82  5016.8 2146.21  5043.2 2145.85  5057.4 2148.24
  5064.1 2150.26  5071.6 2149.76  5078.3 2151.20  5085.8 2149.01  5092.5 2152.26
  5100.1 2148.73  5106.7 2149.56  5121.0 2148.43  5127.8 2145.94  5135.2 2144.85
  5156.1 2157.07  5163.6 2160.17  5170.3 2161.80  5177.8 2162.11  5201.1 2165.53
#Mann=4,-1,0
  4834.3    0.07       0  4992.5    0.07       0  4996.5    0.07       0
  5016.8    0.16       0
Bank Sta=4992.5,4996.5
Exp/Cntr=0.3,0.1

Type RM Length L Ch R = 1,4608,107,107,107
BEGIN DESCRIPTION:
Elm 76 4608.18
END DESCRIPTION:
XS GIS Cut Line= 3
      1530126.22      6761759.68      1530213.43      6761673.77
      1530290.14      6761508.64
#Sta/Elev= 30
  4886.4 2184.57  4929.1 2182.48  4936.2 2181.29  4943.3 2181.95  4950.4 2180.64
  4957.4 2181.54  4964.5 2178.52  4971.6 2164.64  4978.7 2157.26  4985.7 2136.94
  4999.8 2137.04  5008.8 2138.85  5015.2 2136.27  5022.6 2136.90  5026.1 2136.23
  5026.3 2135.73  5030.1 2136.23  5031.0 2136.40  5045.5 2139.67  5051.0 2136.45
  5068.3 2139.96  5081.3 2141.44  5091.2 2145.31  5136.5 2144.79  5142.5 2147.24
  5148.1 2147.49  5158.5 2153.81  5165.4 2159.32  5180.6 2163.22  5190.9 2164.27
#Mann=4,-1,0
  4886.4    0.07       0  5026.1    0.07       0  5030.1    0.07       0
  5031.0    0.16       0
Bank Sta=5026.1,5030.1
Exp/Cntr=0.3,0.1

Type RM Length L Ch R = 1,4501,88,88,88
BEGIN DESCRIPTION:
Elm 76 4500.89
END DESCRIPTION:
XS GIS Cut Line= 3
      1530179.58      6761753.19      1530299.36      6761641.22
      1530417.85      6761553.98
#Sta/Elev= 30
  4834.6 2182.77  4863.4 2180.32  4870.2 2175.17  4877.5 2172.77  4884.4 2167.28
  4891.7 2165.29  4898.5 2159.68  4905.9 2158.30  4912.7 2151.39  4920.0 2151.24
  4929.0 2147.61  4948.4 2145.75  4962.5 2142.89  4969.4 2138.81  4976.7 2138.40
  4983.5 2135.40  4988.9 2135.21  4989.1 2134.71  4992.9 2135.21  4997.3 2138.05
  5005.6 2138.78  5012.1 2142.09  5018.3 2143.41  5026.7 2149.85  5032.9 2148.80
  5041.4 2153.09  5047.6 2154.66  5127.0 2161.36  5142.6 2166.81  5145.7 2166.81
#Mann=5,-1,0
  4834.6    0.07       0  4929.0    0.16       0  4988.9    0.07       0
  4992.9    0.16       0  5142.6    0.07       0
Bank Sta=4988.9,4992.9
Exp/Cntr=0.3,0.1

Type RM Length L Ch R = 1,4413,65,65,65
BEGIN DESCRIPTION:
Elm 76 4413.21
END DESCRIPTION:
XS GIS Cut Line= 3
      1530182.18      6761783.14      1530356.66      6761703.72
      1530489.45      6761604.77
#Sta/Elev= 30
  4810.8 2179.05  4815.3 2180.56  4832.8 2178.58  4838.3 2181.11  4855.9 2178.32
  4861.4 2179.47  4878.9 2171.98  4884.4 2173.78  4901.8 2165.22  4907.5 2160.47
  4913.0 2159.91  4922.6 2155.19  4930.5 2148.76  4945.7 2141.60  4959.1 2140.11
  4967.7 2135.77  4987.7 2134.20  4987.9 2133.70  4991.7 2134.20  5005.2 2138.89
  5019.8 2148.12  5034.4 2151.65  5105.3 2157.83  5119.9 2156.43  5126.1 2159.55
  5134.5 2158.18  5139.2 2160.04  5149.1 2158.85  5155.3 2161.93  5168.1 2162.00
#Mann=5,-1,0
  4810.8    0.07       0  4922.6    0.16       0  4987.7    0.07       0
  4991.7    0.16       0  5139.2    0.07       0
Bank Sta=4987.7,4991.7
Exp/Cntr=0.3,0.1

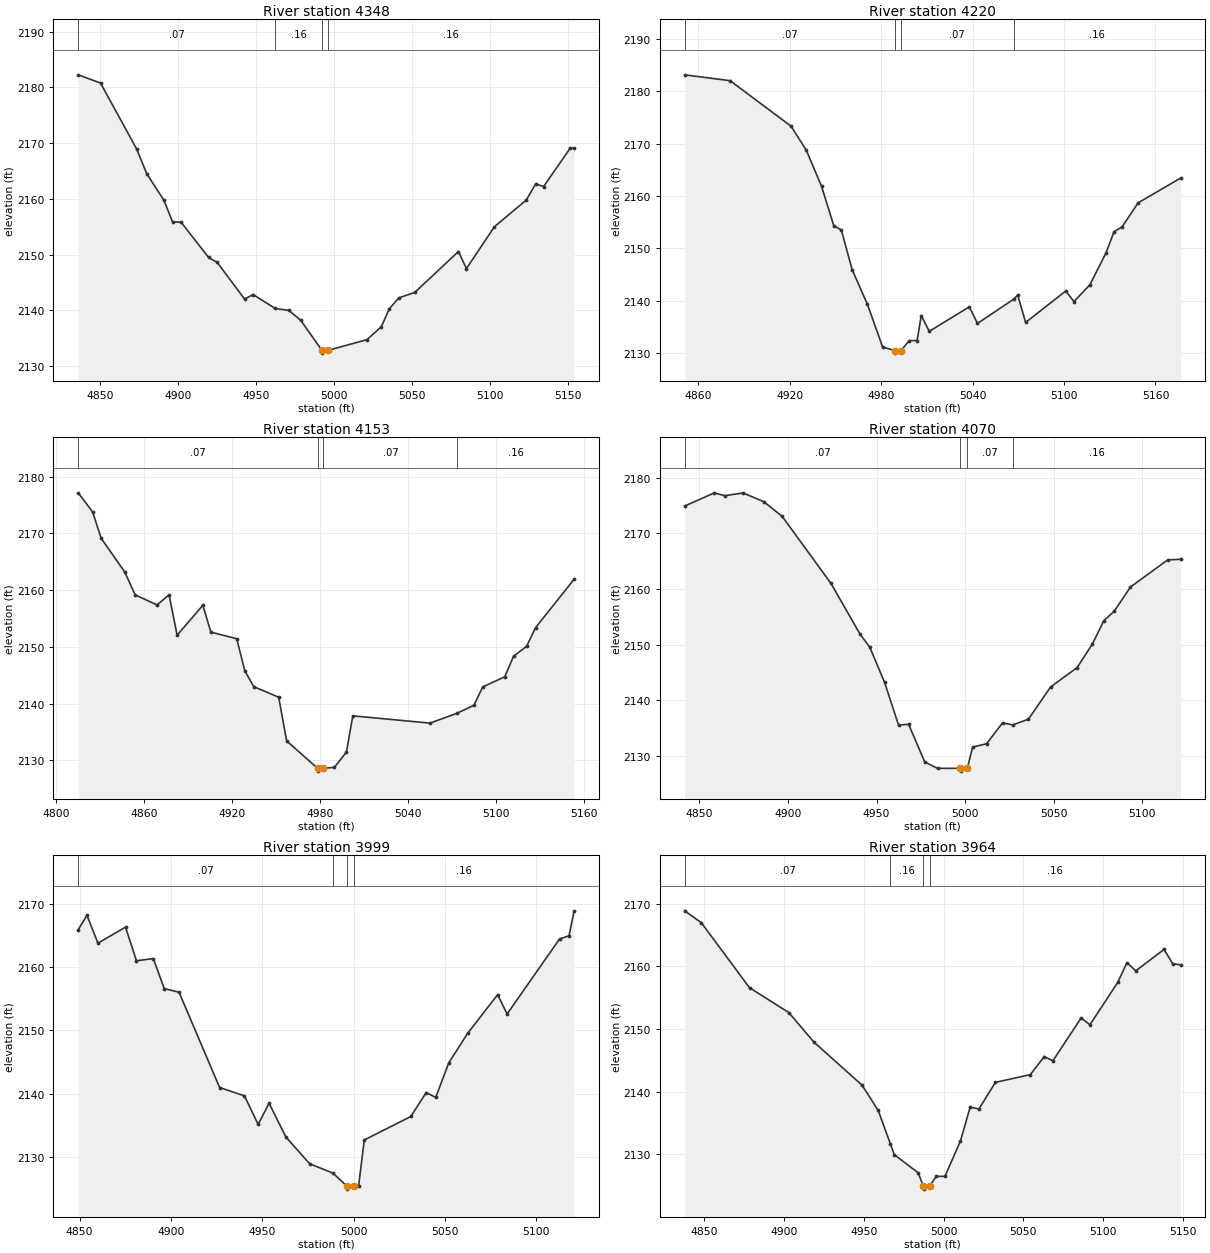
Type RM Length L Ch R = 1,4348,128,128,128
BEGIN DESCRIPTION:
Elm 76 4347.723
END DESCRIPTION:
XS GIS Cut Line= 3
      1530204.96      6761838.02      1530354.49      6761770.18
      1530504.99      6761738.00
#Sta/Elev= 30
  4835.8 2182.25  4850.1 2180.78  4873.2 2168.98  4879.8 2164.47  4890.8 2159.73
  4896.3 2155.86  4901.8 2155.80  4919.4 2149.48  4924.9 2148.60  4942.5 2142.00
  4948.0 2142.81  4962.2 2140.31  4971.0 2139.96  4978.6 2138.17  4992.1 2132.80
  4992.4 2132.30  4996.1 2132.80  5021.0 2134.72  5030.2 2137.03  5035.3 2140.24
  5041.4 2142.21  5051.7 2143.20  5079.7 2150.54  5084.8 2147.47  5102.8 2155.00
  5123.2 2159.78  5129.2 2162.66  5134.3 2162.20  5151.4 2169.09  5153.9 2169.09
#Mann=4,-1,0
  4835.8    0.07       0  4962.2    0.16       0  4992.1    0.07       0
  4996.1    0.16       0
Bank Sta=4992.1,4996.1
Exp/Cntr=0.3,0.1

Type RM Length L Ch R = 1,4220,67,67,67
BEGIN DESCRIPTION:
Elm 76 4220
END DESCRIPTION:
XS GIS Cut Line= 3
      1530165.21      6761879.50      1530314.99      6761884.71
      1530481.51      6761829.20
#Sta/Elev= 30
  4851.1 2183.10  4880.9 2181.98  4920.9 2173.31  4930.9 2168.72  4940.9 2161.85
  4948.9 2154.35  4953.9 2153.51  4961.0 2145.94  4971.0 2139.34  4981.0 2131.20
  4989.0 2130.54  4989.2 2130.04  4993.0 2130.54  4998.5 2132.43  5003.6 2132.43
  5006.3 2137.20  5011.6 2134.20  5037.9 2138.87  5043.2 2135.70  5066.9 2140.31
  5069.6 2141.11  5074.8 2135.89  5101.2 2141.90  5106.5 2139.87  5116.9 2143.05
  5127.5 2149.11  5132.8 2153.18  5138.1 2154.11  5148.6 2158.69  5176.5 2163.41
#Mann=4,-1,0
  4851.1    0.07       0  4989.0    0.07       0  4993.0    0.07       0
  5066.9    0.16       0
Bank Sta=4989,4993
Exp/Cntr=0.3,0.1

Type RM Length L Ch R = 1,4153,83,83,83
BEGIN DESCRIPTION:
Elm 76 4153.15
END DESCRIPTION:
XS GIS Cut Line= 3
      1530186.10      6762009.70      1530357.96      6761931.58
      1530481.44      6761847.97
#Sta/Elev= 30
  4815.3 2177.16  4825.1 2173.80  4831.0 2169.12  4847.0 2163.21  4854.1 2159.18
  4869.0 2157.41  4877.2 2159.19  4882.7 2152.07  4900.2 2157.34  4905.7 2152.61
  4923.3 2151.45  4928.8 2145.80  4934.9 2143.01  4951.9 2141.14  4957.3 2133.45
  4978.4 2128.62  4978.7 2128.12  4982.4 2128.62  4989.8 2128.78  4998.0 2131.45
  5002.4 2137.86  5055.0 2136.58  5073.5 2138.33  5084.9 2139.72  5090.9 2142.95
  5105.9 2144.74  5111.9 2148.35  5120.8 2150.12  5126.9 2153.40  5153.2 2161.94
#Mann=4,-1,0
  4815.3    0.07       0  4978.4    0.07       0  4982.4    0.07       0
  5073.5    0.16       0
Bank Sta=4978.4,4982.4
Exp/Cntr=0.3,0.1

Type RM Length L Ch R = 1,4070,71,71,71
BEGIN DESCRIPTION:
Elm 76 4069.99
END DESCRIPTION:
XS GIS Cut Line= 3
      1530361.87      6762077.41      1530438.69      6761934.19
      1530503.79      6761836.52
#Sta/Elev= 30
  4841.7 2174.89  4858.5 2177.26  4864.2 2176.75  4874.7 2177.23  4886.4 2175.66
  4896.7 2173.04  4924.3 2160.98  4940.5 2151.97  4946.2 2149.51  4954.5 2143.24
  4962.4 2135.56  4968.1 2135.68  4977.2 2128.92  4984.4 2127.78  4997.2 2127.78
  4997.5 2127.28  5001.2 2127.78  5004.2 2131.59  5012.1 2132.20  5021.1 2135.95
  5026.8 2135.58  5035.7 2136.60  5048.2 2142.39  5063.2 2145.88  5071.8 2150.10
  5078.2 2154.26  5084.2 2156.03  5093.3 2160.34  5114.3 2165.22  5121.6 2165.32
#Mann=4,-1,0
  4841.7    0.07       0  4997.2    0.07       0  5001.2    0.07       0
  5026.8    0.16       0
Bank Sta=4997.2,5001.2
Exp/Cntr=0.3,0.1

Type RM Length L Ch R = 1,3999,35,35,35
BEGIN DESCRIPTION:
Elm 76 3999.15
END DESCRIPTION:
XS GIS Cut Line= 3
      1530425.66      6762064.40      1530509.00      6761935.49
      1530541.25      6761821.98
#Sta/Elev= 30
  4849.2 2165.89  4854.0 2168.16  4860.0 2163.76  4875.1 2166.29  4881.1 2160.99
  4890.3 2161.33  4896.3 2156.60  4904.4 2156.03  4926.6 2141.01  4940.2 2139.69
  4947.7 2135.20  4953.7 2138.52  4962.9 2133.20  4975.9 2128.99  4988.7 2127.51
  4996.2 2125.49  4996.5 2124.99  5000.2 2125.49  5002.7 2125.49  5005.8 2132.74
  5031.3 2136.44  5039.7 2140.22  5044.9 2139.45  5052.1 2144.92  5062.5 2149.59
  5078.8 2155.64  5084.0 2152.60  5112.7 2164.42  5117.9 2164.93  5120.7 2168.86
#Mann=4,-1,0
  4849.2    0.07       0  4988.7    0.16       0  4996.2    0.07       0
  5000.2    0.16       0
Bank Sta=4996.2,5000.2
Exp/Cntr=0.3,0.1

Type RM Length L Ch R = 1,3964,78,78,78
BEGIN DESCRIPTION:
Elm 76 3963.78
END DESCRIPTION:
XS GIS Cut Line= 3
      1530522.02      6762098.28      1530541.55      6761940.70
      1530603.69      6761802.19
#Sta/Elev= 30
  4837.9 2168.86  4848.3 2166.97  4878.5 2156.59  4903.2 2152.61  4918.8 2147.92
  4949.0 2141.04  4959.1 2137.00  4966.7 2131.70  4969.2 2129.95  4984.2 2127.04
  4987.3 2124.95  4987.6 2124.45  4991.3 2124.95  4995.5 2126.49  5000.9 2126.49
  5010.6 2132.13  5016.7 2137.54  5022.2 2137.24  5032.5 2141.49  5054.4 2142.72
  5063.1 2145.61  5068.5 2144.93  5086.2 2151.77  5091.7 2150.68  5109.2 2157.47
  5114.9 2160.60  5120.4 2159.28  5138.1 2162.70  5143.6 2160.41  5148.5 2160.24
#Mann=4,-1,0
  4837.9    0.07       0  4966.7    0.16       0  4987.3    0.07       0
  4991.3    0.16       0
Bank Sta=4987.3,4991.3
Exp/Cntr=0.3,0.1

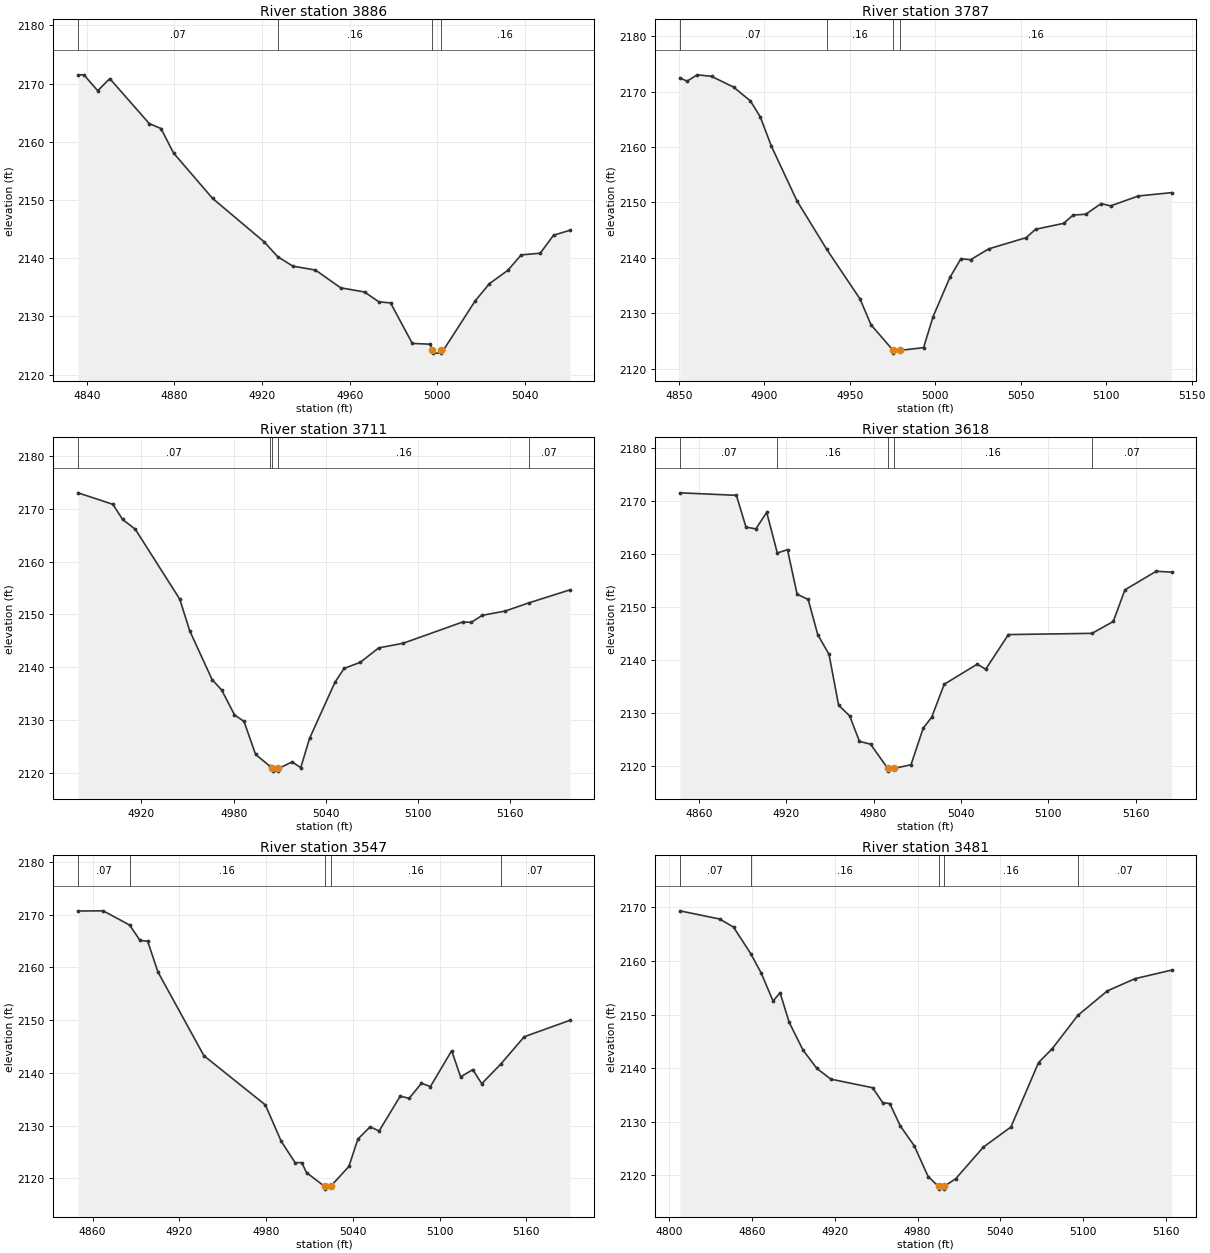
Type RM Length L Ch R = 1,3886,99,99,99
BEGIN DESCRIPTION:
Elm 76 3886.478
END DESCRIPTION:
XS GIS Cut Line= 3
      1530555.00      6762087.99      1530620.20      6761937.51
      1530654.99      6761888.01
#Sta/Elev= 30
  4836.0 2171.50  4838.7 2171.50  4845.0 2168.77  4850.5 2170.85  4868.5 2163.14
  4873.9 2162.27  4879.6 2158.08  4897.4 2150.29  4920.9 2142.84  4927.2 2140.25
  4934.1 2138.64  4944.4 2137.97  4955.9 2134.92  4966.8 2134.20  4973.3 2132.52
  4978.7 2132.32  4988.6 2125.37  4996.8 2125.23  4997.7 2124.20  4998.0 2123.70
  5001.5 2123.70  5001.7 2124.20  5002.8 2124.20  5017.4 2132.72  5023.8 2135.63
  5032.2 2137.91  5038.3 2140.57  5047.0 2140.86  5053.1 2143.95  5060.5 2144.79
#Mann=4,-1,0
  4836.0    0.07       0  4927.2    0.16       0  4997.7    0.07       0
  5001.7    0.16       0
Bank Sta=4997.7,5001.7
Exp/Cntr=0.3,0.1

Type RM Length L Ch R = 1,3787,76,76,76
BEGIN DESCRIPTION:
Elm 76 3786.89
END DESCRIPTION:
XS GIS Cut Line= 3
      1530626.18      6762113.88      1530696.50      6761996.69
      1530768.13      6761863.84
#Sta/Elev= 30
  4850.7 2172.50  4854.9 2171.90  4860.8 2173.05  4869.2 2172.78  4882.1 2170.83
  4891.9 2168.35  4897.7 2165.47  4904.2 2160.17  4919.1 2150.33  4936.5 2141.56
  4956.0 2132.59  4962.5 2127.89  4975.4 2123.28  4975.6 2122.78  4979.4 2123.28
  4993.2 2123.77  4998.8 2129.39  5008.6 2136.45  5015.1 2139.85  5020.7 2139.65
  5031.3 2141.61  5053.2 2143.64  5058.8 2145.16  5075.1 2146.22  5080.7 2147.72
  5088.1 2147.87  5097.0 2149.79  5102.6 2149.38  5118.9 2151.17  5138.3 2151.77
#Mann=4,-1,0
  4850.7    0.07       0  4936.5    0.16       0  4975.4    0.07       0
  4979.4    0.16       0
Bank Sta=4975.4,4979.4
Exp/Cntr=0.3,0.1

Type RM Length L Ch R = 1,3711,93,93,93
BEGIN DESCRIPTION:
Elm 76 3711.36
END DESCRIPTION:
XS GIS Cut Line= 3
      1530686.07      6762130.82      1530759.00      6762034.45
      1530850.09      6761857.47
#Sta/Elev= 30
  4878.7 2173.00  4901.4 2170.83  4907.7 2167.97  4916.0 2166.11  4944.9 2152.89
  4951.4 2146.90  4965.9 2137.71  4972.2 2135.70  4980.5 2131.03  4986.7 2129.78
  4994.2 2123.56  5003.4 2121.35  5005.1 2120.89  5005.3 2120.39  5008.8 2120.39
  5009.1 2120.89  5018.0 2122.13  5023.6 2121.05  5029.3 2126.56  5045.8 2137.16
  5051.8 2139.80  5062.4 2140.97  5074.3 2143.69  5090.2 2144.56  5128.9 2148.58
  5134.5 2148.52  5141.8 2149.85  5156.7 2150.66  5171.8 2152.18  5198.6 2154.65
#Mann=5,-1,0
  4878.7    0.07       0  5003.4    0.16       0  5005.1    0.07       0
  5009.1    0.16       0  5171.8    0.07       0
Bank Sta=5005.1,5009.1
Exp/Cntr=0.3,0.1

Type RM Length L Ch R = 1,3618,71,71,71
BEGIN DESCRIPTION:
Elm 76 3618.22
END DESCRIPTION:
XS GIS Cut Line= 3
      1530735.53      6762142.55      1530851.45      6762042.26
      1530945.18      6761883.44
#Sta/Elev= 30
  4847.0 2171.58  4885.8 2171.11  4892.4 2165.11  4899.2 2164.78  4906.6 2167.90
  4913.9 2160.23  4920.9 2160.85  4927.5 2152.44  4935.1 2151.46  4941.7 2144.80
  4949.4 2141.11  4956.0 2131.50  4963.6 2129.48  4970.3 2124.68  4977.9 2124.15
  4989.8 2119.56  4990.0 2119.06  4993.8 2119.56  5005.7 2120.26  5014.1 2127.17
  5019.9 2129.22  5028.5 2135.45  5051.2 2139.25  5057.0 2138.29  5072.6 2144.83
  5130.0 2145.06  5144.6 2147.30  5152.6 2153.27  5174.1 2156.78  5184.7 2156.61
#Mann=5,-1,0
  4847.0    0.07       0  4913.9    0.16       0  4989.8    0.07       0
  4993.8    0.16       0  5130.0    0.07       0
Bank Sta=4989.8,4993.8
Exp/Cntr=0.3,0.1

Type RM Length L Ch R = 1,3547,66,66,66
BEGIN DESCRIPTION:
Elm 76 3547.33
END DESCRIPTION:
XS GIS Cut Line= 3
      1530762.94      6762138.60      1530908.74      6762086.53
      1531018.09      6761936.83
#Sta/Elev= 30
  4849.9 2170.67  4867.3 2170.70  4885.6 2168.01  4892.8 2165.09  4898.1 2164.94
  4905.2 2159.11  4937.0 2143.25  4979.5 2133.92  4990.5 2127.02  5000.1 2122.98
  5004.7 2122.98  5008.0 2121.08  5020.6 2118.46  5020.9 2117.96  5024.6 2118.46
  5037.3 2122.26  5043.5 2127.44  5052.0 2129.77  5058.2 2128.98  5072.8 2135.58
  5079.0 2135.17  5087.5 2138.02  5093.7 2137.40  5108.4 2144.19  5114.6 2139.23
  5123.0 2140.61  5129.2 2137.94  5142.3 2141.64  5158.6 2146.84  5190.1 2149.94
#Mann=5,-1,0
  4849.9    0.07       0  4885.6    0.16       0  5020.6    0.07       0
  5024.6    0.16       0  5142.3    0.07       0
Bank Sta=5020.6,5024.6
Exp/Cntr=0.3,0.1

Type RM Length L Ch R = 1,3481,84,84,84
BEGIN DESCRIPTION:
Elm 76 3480.74
END DESCRIPTION:
XS GIS Cut Line= 3
      1530756.37      6762162.05      1530949.10      6762137.31
      1531111.54      6762133.44
#Sta/Elev= 30
  4807.6 2169.34  4836.5 2167.81  4846.5 2166.31  4859.0 2161.36  4866.7 2157.69
  4875.2 2152.51  4880.3 2154.07  4886.9 2148.55  4897.0 2143.35  4907.0 2139.95
  4917.1 2137.96  4947.4 2136.36  4954.8 2133.56  4959.9 2133.41  4967.5 2129.24
  4977.6 2125.55  4987.7 2119.80  4995.3 2117.95  4995.6 2117.45  4999.1 2117.45
  4999.3 2117.95  5007.8 2119.41  5027.8 2125.29  5047.8 2129.03  5067.8 2141.04
  5077.8 2143.65  5096.3 2149.84  5117.8 2154.42  5137.8 2156.69  5164.4 2158.29
#Mann=5,-1,0
  4807.6    0.07       0  4859.0    0.16       0  4995.3    0.07       0
  4999.3    0.16       0  5096.3    0.07       0
Bank Sta=4995.3,4999.3
Exp/Cntr=0.3,0.1

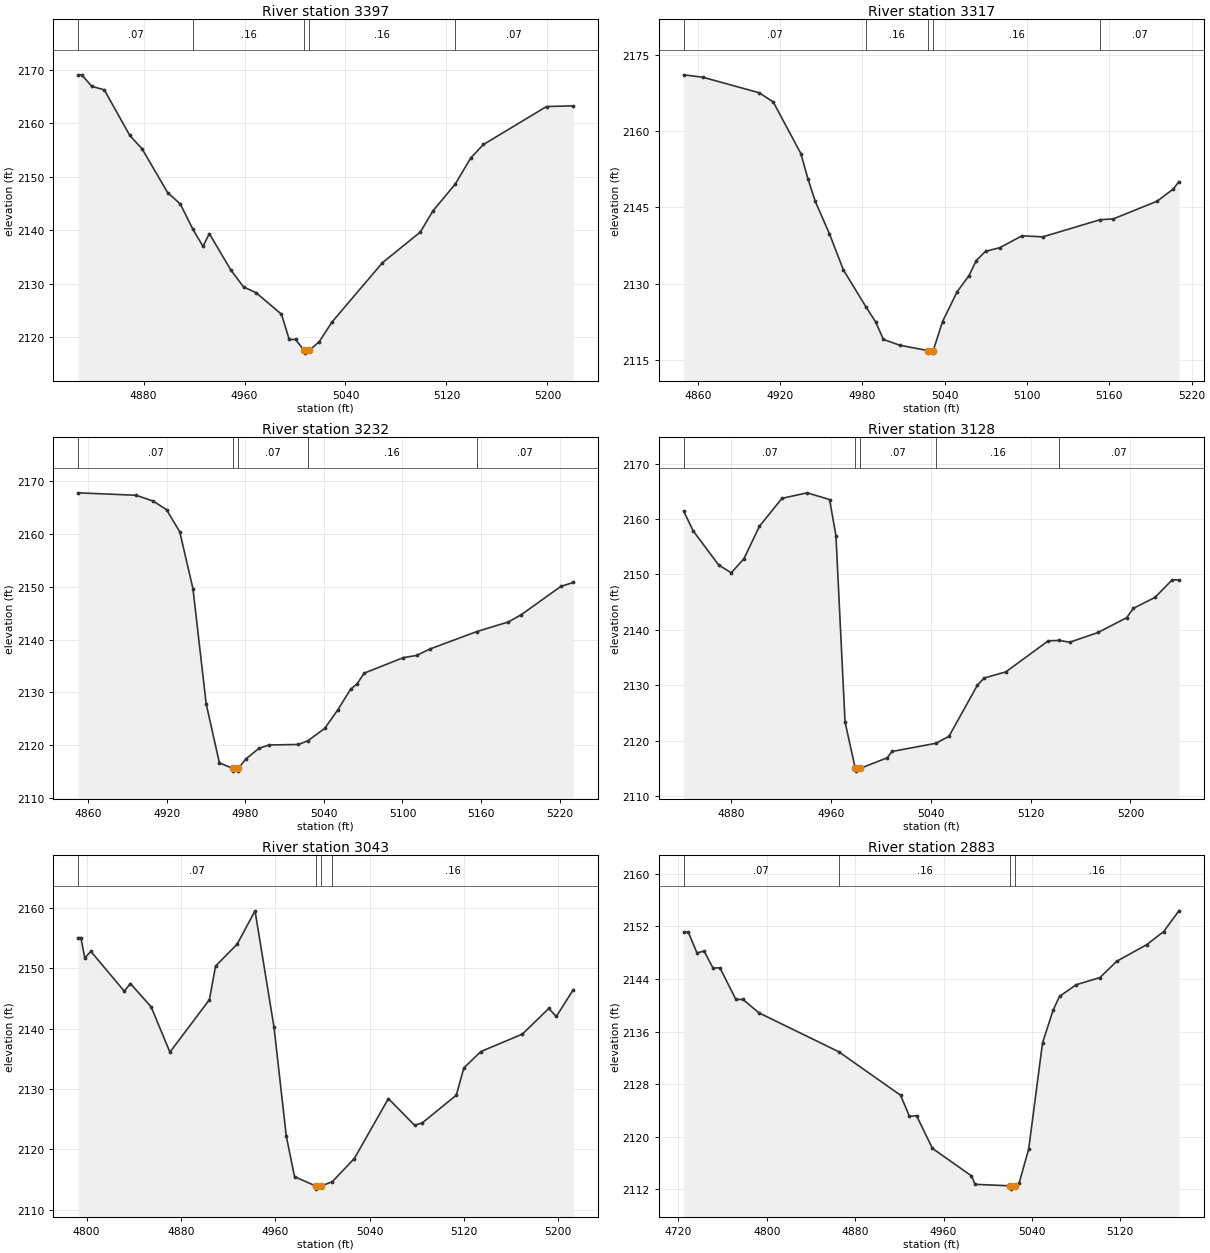
Type RM Length L Ch R = 1,3397,80,80,80
BEGIN DESCRIPTION:
Elm 76 3397.37
END DESCRIPTION:
XS GIS Cut Line= 3
      1530734.31      6762195.91      1530902.23      6762207.62
      1531126.17      6762203.72
#Sta/Elev= 30
  4828.2 2169.11  4831.0 2169.11  4838.9 2166.97  4848.9 2166.29  4869.0 2157.80
  4879.0 2155.19  4899.1 2147.04  4909.1 2144.93  4919.0 2140.22  4927.1 2136.98
  4932.1 2139.37  4949.2 2132.54  4959.2 2129.39  4969.2 2128.29  4989.3 2124.26
  4995.4 2119.54  5000.4 2119.54  5007.3 2117.48  5007.6 2116.98  5011.3 2117.48
  5019.3 2119.15  5029.3 2122.80  5069.3 2133.92  5099.3 2139.66  5109.3 2143.63
  5126.9 2148.62  5139.3 2153.56  5149.3 2156.06  5199.3 2163.17  5220.5 2163.30
#Mann=5,-1,0
  4828.2    0.07       0  4919.0    0.16       0  5007.3    0.07       0
  5011.3    0.16       0  5126.9    0.07       0
Bank Sta=5007.3,5011.3
Exp/Cntr=0.3,0.1

Type RM Length L Ch R = 1,3317,85,85,85
BEGIN DESCRIPTION:
Elm 76 3317.1
END DESCRIPTION:
XS GIS Cut Line= 3
      1530721.28      6762244.09      1530867.07      6762275.33
      1531070.13      6762335.21
#Sta/Elev= 30
  4849.8 2171.05  4863.8 2170.57  4904.7 2167.53  4915.0 2165.72  4935.2 2155.54
  4940.3 2150.60  4945.6 2146.20  4955.9 2139.84  4966.1 2132.72  4982.5 2125.46
  4989.7 2122.44  4995.3 2119.02  5007.2 2117.89  5027.6 2116.83  5027.9 2116.33
  5031.4 2116.33  5031.6 2116.83  5038.4 2122.54  5048.9 2128.34  5057.7 2131.59
  5062.9 2134.51  5069.7 2136.35  5080.1 2137.06  5096.3 2139.40  5111.4 2139.19
  5153.2 2142.56  5162.9 2142.73  5194.8 2146.21  5206.6 2148.61  5210.6 2150.05
#Mann=5,-1,0
  4849.8    0.07       0  4982.5    0.16       0  5027.6    0.07       0
  5031.6    0.16       0  5153.2    0.07       0
Bank Sta=5027.6,5031.6
Exp/Cntr=0.3,0.1

Type RM Length L Ch R = 1,3232,104,104,104
BEGIN DESCRIPTION:
Elm 76 3232.28
END DESCRIPTION:
XS GIS Cut Line= 3
      1530708.20      6762336.53      1530855.35      6762357.36
      1531084.50      6762341.74
#Sta/Elev= 30
  4852.2 2167.75  4896.4 2167.29  4909.6 2166.18  4919.7 2164.56  4929.8 2160.39
  4939.9 2149.62  4950.0 2127.84  4960.1 2116.67  4970.5 2115.60  4970.7 2115.10
  4974.2 2115.10  4974.5 2115.60  4980.3 2117.40  4990.4 2119.42  4998.1 2120.05
  5020.5 2120.14  5027.9 2120.87  5040.6 2123.19  5050.6 2126.70  5060.3 2130.59
  5065.3 2131.59  5070.6 2133.62  5100.7 2136.58  5110.7 2136.98  5120.7 2138.18
  5156.6 2141.49  5180.9 2143.32  5190.9 2144.72  5221.0 2150.05  5230.5 2150.79
#Mann=5,-1,0
  4852.2    0.07       0  4970.5    0.07       0  4974.5    0.07       0
  5027.9    0.16       0  5156.6    0.07       0
Bank Sta=4970.5,4974.5
Exp/Cntr=0.3,0.1

Type RM Length L Ch R = 1,3128,85,85,85
BEGIN DESCRIPTION:
Elm 76 3127.6
END DESCRIPTION:
XS GIS Cut Line= 3
      1530717.36      6762482.36      1530876.19      6762456.32
      1531089.77      6762356.04
#Sta/Elev= 30
  4841.9 2161.40  4849.6 2157.82  4869.9 2151.70  4880.0 2150.29  4890.2 2152.86
  4902.6 2158.70  4920.6 2163.73  4940.8 2164.73  4958.8 2163.52  4963.9 2157.01
  4971.2 2123.37  4979.4 2114.98  4979.6 2114.48  4983.4 2114.98  5005.0 2116.89
  5008.9 2118.03  5044.1 2119.51  5054.5 2120.76  5077.3 2130.00  5082.8 2131.30
  5100.1 2132.40  5134.1 2138.00  5143.0 2138.09  5151.3 2137.75  5174.1 2139.52
  5196.9 2142.18  5202.4 2143.88  5219.7 2145.85  5233.4 2149.01  5238.8 2149.01
#Mann=5,-1,0
  4841.9    0.07       0  4979.4    0.07       0  4983.4    0.07       0
  5044.1    0.16       0  5143.0    0.07       0
Bank Sta=4979.4,4983.4
Exp/Cntr=0.3,0.1

Type RM Length L Ch R = 1,3043,160,160,160
BEGIN DESCRIPTION:
Elm 76 3042.76
END DESCRIPTION:
XS GIS Cut Line= 3
      1530735.55      6762574.81      1530932.18      6762517.52
      1531100.14      6762383.15
#Sta/Elev= 30
  4792.9 2155.11  4795.2 2155.11  4798.5 2151.76  4803.7 2152.83  4832.0 2146.23
  4837.2 2147.50  4854.8 2143.63  4870.7 2136.12  4904.2 2144.82  4909.4 2150.39
  4927.7 2154.03  4942.9 2159.56  4959.0 2140.23  4969.4 2122.18  4976.4 2115.47
  4994.6 2113.90  4994.8 2113.40  4998.6 2113.90  5008.4 2114.63  5027.1 2118.48
  5056.0 2128.42  5078.2 2123.99  5084.8 2124.40  5113.6 2128.99  5120.0 2133.51
  5134.4 2136.22  5169.6 2139.11  5192.0 2143.36  5198.4 2142.04  5212.8 2146.49
#Mann=4,-1,0
  4792.9    0.07       0  4994.6    0.07       0  4998.6    0.07       0
  5008.4    0.16       0
Bank Sta=4994.6,4998.6
Exp/Cntr=0.3,0.1

Type RM Length L Ch R = 1,2883,89,89,89
BEGIN DESCRIPTION:
Elm 76 2883.2
END DESCRIPTION:
XS GIS Cut Line= 3
      1530873.61      6762712.81      1531080.61      6762548.77
      1531178.12      6762392.76
#Sta/Elev= 30
  4724.9 2151.14  4729.0 2151.14  4736.9 2147.97  4743.3 2148.25  4751.3 2145.70
  4757.7 2145.68  4772.1 2140.88  4778.5 2140.89  4792.9 2138.85  4865.2 2132.92
  4921.1 2126.30  4929.2 2123.08  4935.6 2123.18  4950.0 2118.20  4985.2 2114.03
  4988.6 2112.73  5020.5 2112.50  5020.8 2112.00  5024.5 2112.50  5028.4 2112.89
  5037.1 2118.11  5049.6 2134.25  5059.1 2139.22  5065.0 2141.36  5080.3 2143.14
  5101.5 2144.21  5116.8 2146.70  5144.0 2149.24  5159.3 2151.23  5173.0 2154.38
#Mann=4,-1,0
  4724.9    0.07       0  4865.2    0.16       0  5020.5    0.07       0
  5024.5    0.16       0
Bank Sta=5020.5,5024.5
Exp/Cntr=0.3,0.1

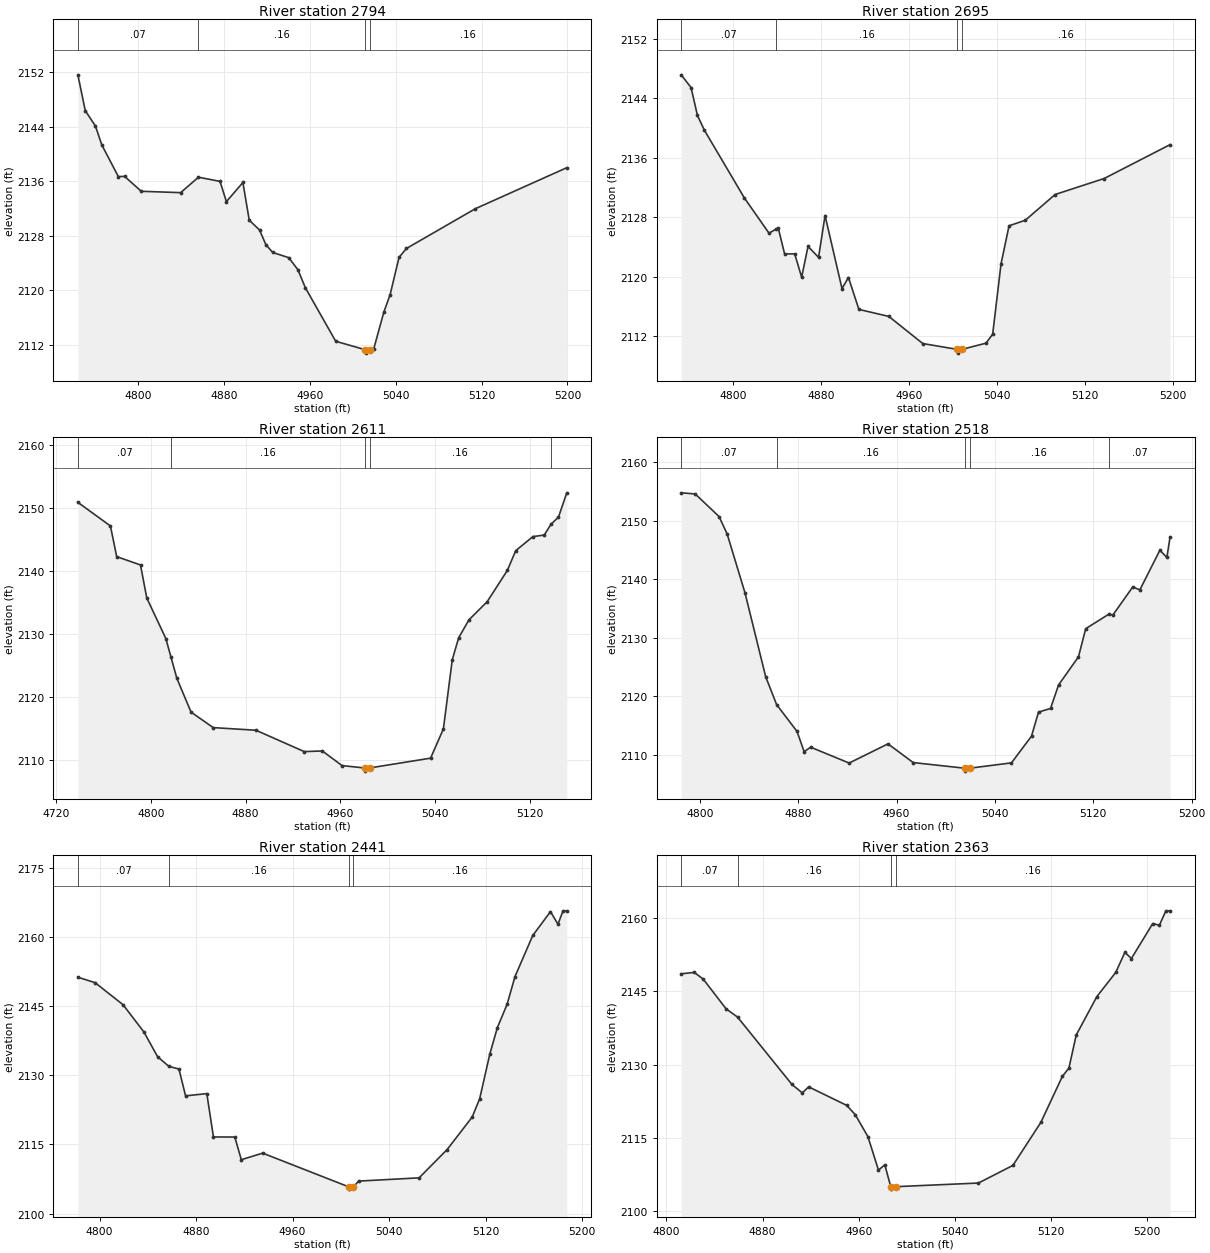
Type RM Length L Ch R = 1,2794,99,99,99
BEGIN DESCRIPTION:
Elm 76 2794.08
END DESCRIPTION:
XS GIS Cut Line= 3
      1530910.05      6762744.08      1531131.40      6762608.67
      1531296.75      6762503.20
#Sta/Elev= 30
  4743.8 2151.61  4750.7 2146.35  4760.2 2144.09  4766.1 2141.33  4781.5 2136.68
  4787.4 2136.70  4802.9 2134.52  4839.6 2134.32  4856.2 2136.59  4876.3 2135.97
  4882.2 2133.00  4897.6 2135.81  4903.5 2130.28  4913.1 2128.84  4919.0 2126.69
  4925.4 2125.54  4940.3 2124.78  4948.9 2123.00  4955.7 2120.39  4984.1 2112.51
  5011.6 2111.27  5011.9 2110.77  5015.6 2111.27  5019.6 2111.44  5028.9 2116.77
  5034.8 2119.36  5043.1 2124.82  5050.0 2126.13  5114.3 2131.97  5199.4 2137.98
#Mann=4,-1,0
  4743.8    0.07       0  4856.2    0.16       0  5011.6    0.07       0
  5015.6    0.16       0
Bank Sta=5011.6,5015.6
Exp/Cntr=0.3,0.1

Type RM Length L Ch R = 1,2695,84,84,84
BEGIN DESCRIPTION:
Elm 76 2695.11
END DESCRIPTION:
XS GIS Cut Line= 3
      1530986.90      6762810.47      1531205.61      6762676.37
      1531312.70      6762521.55
#Sta/Elev= 30
  4752.7 2147.14  4761.7 2145.43  4767.5 2141.67  4773.9 2139.67  4810.1 2130.60
  4832.6 2125.84  4838.9 2126.37  4841.0 2126.54  4846.8 2123.05  4856.0 2123.05
  4862.3 2119.91  4868.1 2124.05  4877.7 2122.59  4883.6 2128.21  4899.0 2118.39
  4904.9 2119.87  4914.4 2115.58  4941.6 2114.64  4972.5 2110.99  5004.0 2110.20
  5004.2 2109.70  5008.0 2110.20  5030.0 2111.04  5036.1 2112.25  5043.7 2121.70
  5051.0 2126.83  5065.8 2127.58  5092.9 2131.04  5137.5 2133.19  5197.5 2137.75
#Mann=4,-1,0
  4752.7    0.07       0  4838.9    0.16       0  5004.0    0.07       0
  5008.0    0.16       0
Bank Sta=5004,5008
Exp/Cntr=0.3,0.1

Type RM Length L Ch R = 1,2611,93,93,93
BEGIN DESCRIPTION:
Elm 76 2611.37
END DESCRIPTION:
XS GIS Cut Line= 3
      1531005.08      6762832.63      1531255.09      6762742.78
      1531391.53      6762687.43
#Sta/Elev= 30
  4738.3 2150.84  4765.8 2147.09  4771.1 2142.22  4791.2 2140.90  4796.5 2135.66
  4812.6 2129.22  4817.0 2126.23  4821.9 2122.90  4833.9 2117.54  4852.6 2115.08
  4888.7 2114.66  4929.5 2111.27  4944.8 2111.37  4961.4 2109.05  4980.6 2108.67
  4980.9 2108.17  4984.6 2108.67  5036.2 2110.23  5047.0 2114.87  5054.5 2125.85
  5059.9 2129.34  5068.6 2132.19  5084.0 2135.07  5101.0 2140.03  5108.1 2143.17
  5122.6 2145.40  5132.2 2145.65  5137.9 2147.37  5144.2 2148.49  5151.2 2152.35
#Mann=5,-1,0
  4738.3    0.07       0  4817.0    0.16       0  4980.6    0.07       0
  4984.6    0.16       0  5137.9    0.07       0
Bank Sta=4980.6,4984.6
Exp/Cntr=0.3,0.1

Type RM Length L Ch R = 1,2518,77,77,77
BEGIN DESCRIPTION:
Elm 76 2518.43
END DESCRIPTION:
XS GIS Cut Line= 3
      1531055.87      6762905.54      1531261.60      6762835.23
      1531420.91      6762751.04
#Sta/Elev= 30
  4784.8 2154.77  4796.2 2154.58  4815.6 2150.72  4822.2 2147.74  4836.7 2137.68
  4853.5 2123.37  4862.4 2118.59  4879.0 2114.01  4884.8 2110.54  4890.1 2111.31
  4921.4 2108.60  4953.0 2111.88  4973.5 2108.68  5015.4 2107.72  5015.6 2107.22
  5019.4 2107.72  5053.4 2108.63  5069.7 2113.19  5075.4 2117.30  5085.2 2117.93
  5091.7 2121.94  5107.9 2126.75  5113.8 2131.56  5132.6 2134.04  5135.8 2133.87
  5152.1 2138.70  5157.8 2138.18  5174.1 2144.96  5179.8 2143.73  5182.4 2147.25
#Mann=5,-1,0
  4784.8    0.07       0  4862.4    0.16       0  5015.4    0.07       0
  5019.4    0.16       0  5132.6    0.07       0
Bank Sta=5015.4,5019.4
Exp/Cntr=0.3,0.1

Type RM Length L Ch R = 1,2441,78,78,78
BEGIN DESCRIPTION:
Elm 76 2440.941
END DESCRIPTION:
XS GIS Cut Line= 3
      1531104.99      6762988.01      1531303.77      6762898.51
      1531455.00      6762788.00
#Sta/Elev= 30
  4782.0 2151.29  4796.3 2150.10  4819.5 2145.31  4836.8 2139.39  4848.1 2134.04
  4857.5 2131.93  4865.8 2131.37  4871.3 2125.55  4888.9 2126.03  4894.4 2116.63
  4912.1 2116.61  4917.5 2111.69  4935.2 2113.12  5006.5 2105.81  5006.8 2105.31
  5010.5 2105.81  5014.7 2107.05  5064.9 2107.76  5088.1 2113.89  5108.9 2120.95
  5115.1 2124.92  5123.6 2134.71  5129.8 2140.37  5137.8 2145.39  5144.4 2151.44
  5159.1 2160.34  5173.8 2165.51  5180.0 2162.79  5184.2 2165.69  5187.3 2165.69
#Mann=4,-1,0
  4782.0    0.07       0  4857.5    0.16       0  5006.5    0.07       0
  5010.5    0.16       0
Bank Sta=5006.5,5010.5
Exp/Cntr=0.3,0.1

Type RM Length L Ch R = 1,2363,76,76,76
BEGIN DESCRIPTION:
Elm 76 2362.67
END DESCRIPTION:
XS GIS Cut Line= 3
      1531127.51      6763035.74      1531312.38      6762974.55
      1531506.37      6762888.62
#Sta/Elev= 30
  4812.3 2148.61  4823.2 2148.90  4830.7 2147.51  4849.7 2141.42  4859.2 2139.74
  4904.5 2125.91  4913.1 2124.18  4918.4 2125.42  4950.1 2121.62  4957.1 2119.74
  4967.7 2115.22  4976.5 2108.35  4981.8 2109.42  4986.7 2104.94  4987.0 2104.44
  4990.7 2104.94  5059.7 2105.69  5088.4 2109.31  5111.7 2118.15  5129.5 2127.55
  5135.0 2129.27  5141.1 2136.06  5158.3 2143.95  5174.0 2148.90  5181.6 2153.02
  5187.0 2151.75  5204.8 2158.93  5210.3 2158.57  5215.7 2161.53  5219.2 2161.53
#Mann=4,-1,0
  4812.3    0.07       0  4859.2    0.16       0  4986.7    0.07       0
  4990.7    0.16       0
Bank Sta=4986.7,4990.7
Exp/Cntr=0.3,0.1