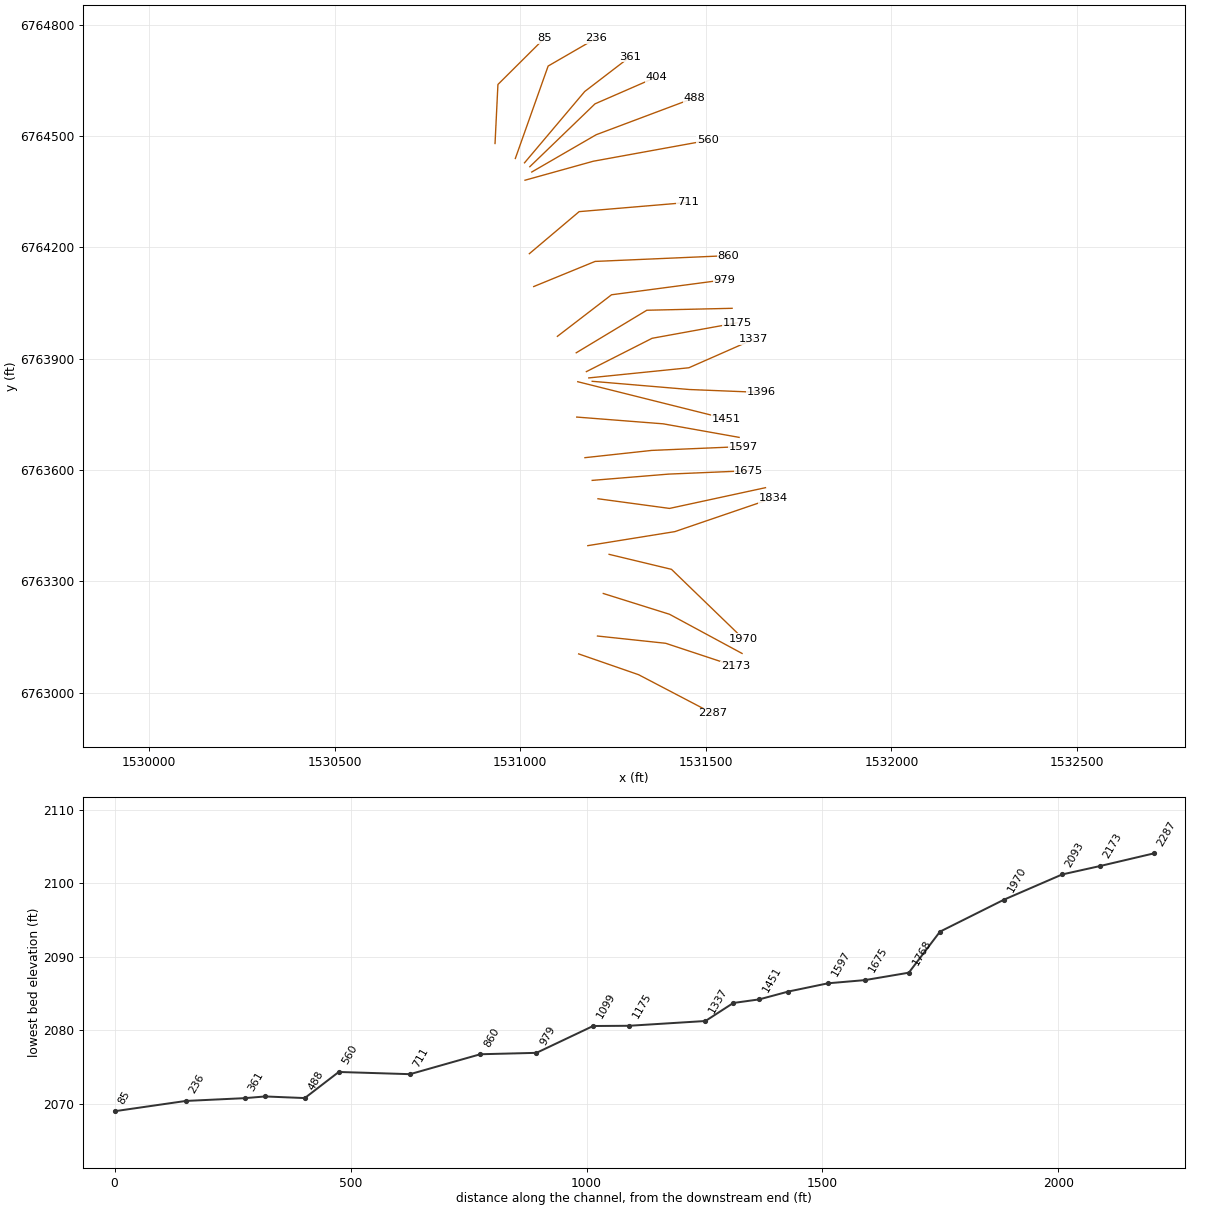
HEC-RAS study Elm 76.prj: Elm 76 Base Level Engineering

--- Elm 76.g01 (geometry) --- (continued)

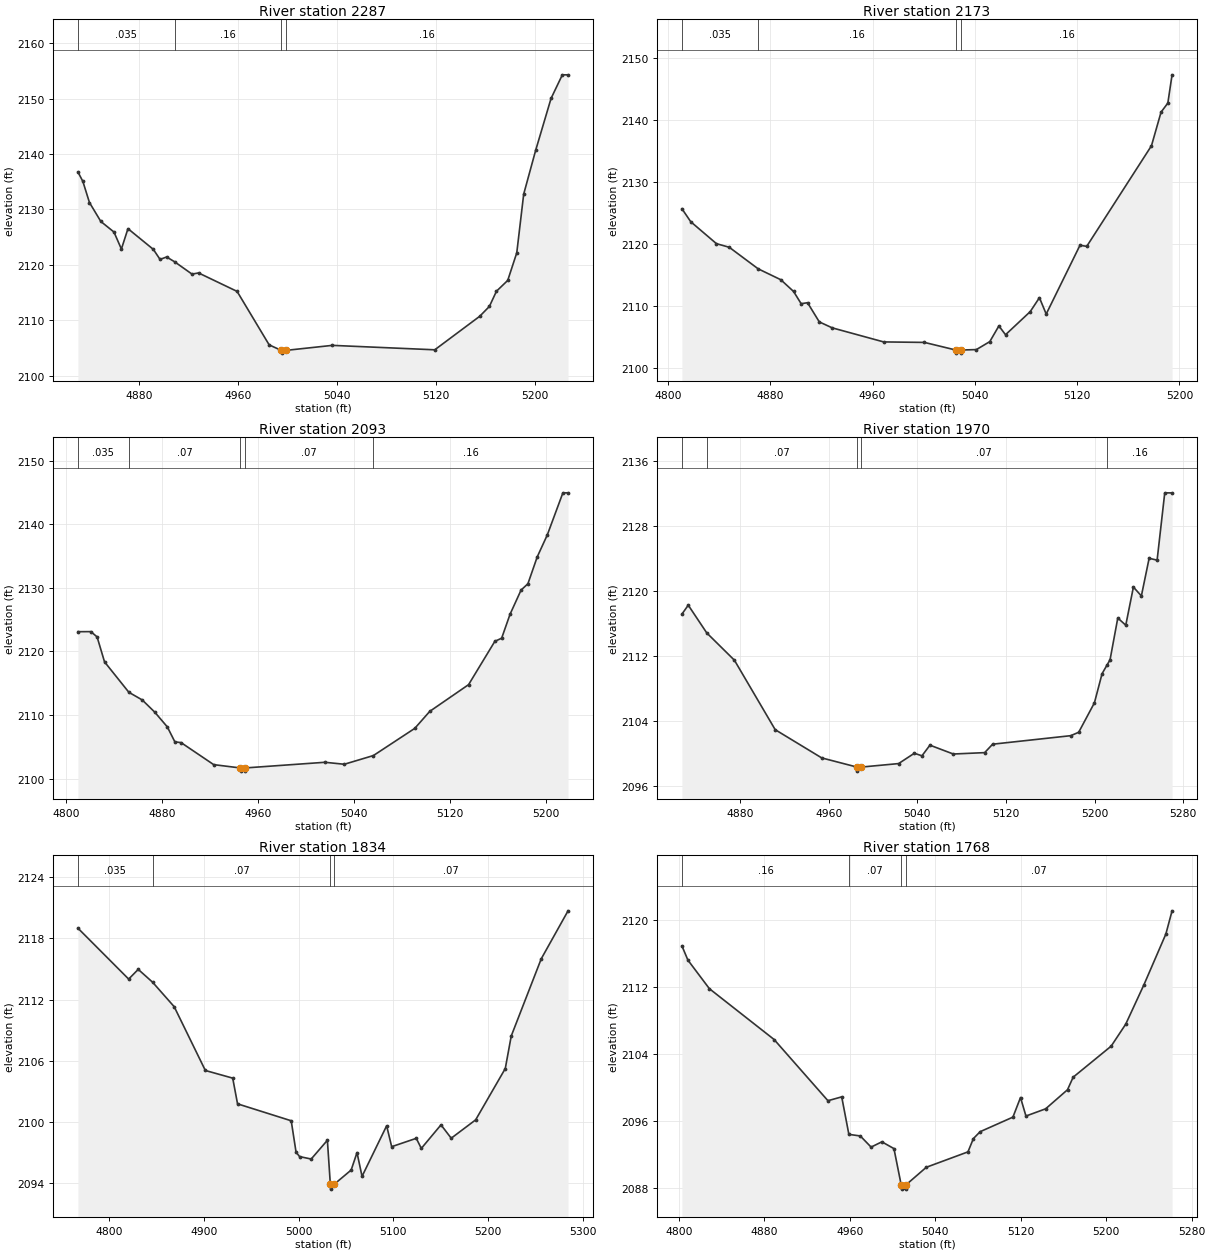
Type RM Length L Ch R = 1,2287,114,114,114
BEGIN DESCRIPTION:
Elm 76 2287.29
END DESCRIPTION:
XS GIS Cut Line= 3
      1531157.48      6763104.75      1531318.90      6763048.77
      1531518.15      6762944.58
#Sta/Elev= 30
  4830.9 2136.75  4834.9 2135.04  4840.2 2131.24  4849.4 2127.82  4860.0 2125.91
  4866.0 2122.84  4871.3 2126.52  4891.8 2122.78  4897.2 2120.97  4902.5 2121.41
  4909.0 2120.54  4923.0 2118.32  4928.3 2118.53  4959.4 2115.20  4985.3 2105.55
  4995.0 2104.56  4995.3 2104.06  4999.0 2104.56  5036.3 2105.46  5119.0 2104.66
  5155.3 2110.71  5163.1 2112.49  5168.8 2115.23  5177.9 2117.18  5185.2 2122.16
  5190.8 2132.76  5200.5 2140.69  5212.9 2150.03  5222.0 2154.28  5226.6 2154.28
#Mann=4,-1,0
  4830.9   0.035       0  4909.0    0.16       0  4995.0    0.07       0
  4999.0    0.16       0
Bank Sta=4995,4999
Exp/Cntr=0.3,0.1

Type RM Length L Ch R = 1,2173,80,80,80
BEGIN DESCRIPTION:
Elm 76 2172.92
END DESCRIPTION:
XS GIS Cut Line= 3
      1531208.18      6763152.94      1531391.81      6763133.40
      1531580.28      6763071.01
#Sta/Elev= 30
  4811.0 2125.65  4817.9 2123.55  4838.0 2120.01  4848.0 2119.43  4870.6 2115.95
  4888.3 2114.19  4898.3 2112.29  4904.2 2110.32  4909.2 2110.48  4918.4 2107.38
  4928.5 2106.42  4968.7 2104.15  5000.6 2104.07  5025.1 2102.84  5025.3 2102.34
  5028.8 2102.34  5029.1 2102.84  5041.2 2102.91  5051.7 2104.20  5058.8 2106.73
  5064.0 2105.31  5083.3 2109.04  5090.5 2111.29  5095.8 2108.65  5122.2 2119.75
  5127.5 2119.58  5178.1 2135.82  5185.6 2141.25  5190.9 2142.71  5194.2 2147.27
#Mann=4,-1,0
  4811.0   0.035       0  4870.6    0.16       0  5025.1    0.07       0
  5029.1    0.16       0
Bank Sta=5025.1,5029.1
Exp/Cntr=0.3,0.1

Type RM Length L Ch R = 1,2093,123,123,123
BEGIN DESCRIPTION:
Elm 76 2092.81
END DESCRIPTION:
XS GIS Cut Line= 3
      1531223.82      6763267.53      1531402.23      6763211.53
      1531597.58      6763106.04
#Sta/Elev= 30
  4809.8 2123.11  4820.6 2123.12  4825.8 2122.29  4832.0 2118.37  4852.3 2113.59
  4863.5 2112.38  4873.9 2110.47  4884.4 2108.15  4890.7 2105.80  4895.9 2105.68
  4923.1 2102.22  4945.3 2101.70  4945.5 2101.20  4949.0 2101.20  4949.3 2101.70
  5015.9 2102.59  5032.1 2102.28  5056.4 2103.65  5090.9 2107.92  5103.4 2110.59
  5135.8 2114.79  5157.7 2121.59  5163.4 2122.09  5170.4 2125.85  5179.6 2129.65
  5185.3 2130.64  5193.1 2134.87  5201.5 2138.32  5214.5 2144.93  5218.8 2144.93
#Mann=5,-1,0
  4809.8   0.035       0  4852.3    0.07       0  4945.3    0.07       0
  4949.3    0.07       0  5056.4    0.16       0
Bank Sta=4945.3,4949.3
Exp/Cntr=0.3,0.1

Type RM Length L Ch R = 1,1970,136,136,136
BEGIN DESCRIPTION:
Elm 76 1969.96
END DESCRIPTION:
XS GIS Cut Line= 3
      1531239.44      6763372.99      1531407.44      6763332.62
      1531601.36      6763145.16
#Sta/Elev= 30
  4827.5 2117.14  4833.2 2118.24  4849.9 2114.82  4874.9 2111.45  4911.7 2102.89
  4953.7 2099.41  4985.5 2098.28  4985.7 2097.78  4989.5 2098.28  5023.1 2098.71
  5037.3 2099.98  5044.2 2099.67  5051.4 2100.98  5072.5 2099.89  5100.8 2100.06
  5108.0 2101.10  5178.5 2102.15  5185.7 2102.57  5199.9 2106.20  5206.8 2109.79
  5211.2 2110.84  5214.0 2111.50  5221.0 2116.66  5228.2 2115.77  5235.1 2120.47
  5242.3 2119.38  5249.3 2124.02  5256.5 2123.79  5263.4 2132.09  5270.0 2132.08
#Mann=5,-1,0
  4827.5   0.035       0  4849.9    0.07       0  4985.5    0.07       0
  4989.5    0.07       0  5211.2    0.16       0
Bank Sta=4985.5,4989.5
Exp/Cntr=0.3,0.1

Type RM Length L Ch R = 1,1834,66,66,66
BEGIN DESCRIPTION:
Elm 76 1833.68
END DESCRIPTION:
XS GIS Cut Line= 3
      1531182.13      6763396.42      1531416.55      6763434.19
      1531681.77      6763524.75
#Sta/Elev= 30
  4766.8 2119.00  4820.4 2114.01  4830.5 2114.96  4845.7 2113.70  4868.5 2111.30
  4901.4 2105.05  4930.3 2104.30  4935.4 2101.78  4992.1 2100.12  4997.2 2097.05
  5000.9 2096.61  5013.2 2096.37  5030.3 2098.21  5033.4 2093.92  5033.7 2093.42
  5037.8 2093.92  5055.4 2095.29  5061.6 2097.00  5066.9 2094.67  5092.9 2099.63
  5098.2 2097.58  5124.2 2098.40  5129.5 2097.41  5150.3 2099.72  5161.1 2098.41
  5186.9 2100.21  5218.2 2105.24  5224.5 2108.43  5256.2 2116.00  5284.5 2120.70
#Mann=4,-1,0
  4766.8   0.035       0  4845.7    0.07       0  5033.4    0.07       0
  5037.8    0.07       0
Bank Sta=5033.4,5037.8
Exp/Cntr=0.3,0.1

Type RM Length L Ch R = 1,1768,93,93,93
BEGIN DESCRIPTION:
Elm 76 1768.38
END DESCRIPTION:
XS GIS Cut Line= 3
      1531209.50      6763522.73      1531402.23      6763496.69
      1531660.68      6763552.53
#Sta/Elev= 30
  4802.7 2116.89  4808.3 2115.19  4828.4 2111.78  4889.0 2105.71  4939.4 2098.40
  4952.3 2098.86  4959.0 2094.38  4969.7 2094.19  4979.8 2092.86  4989.9 2093.49
  5001.2 2092.68  5008.0 2088.34  5008.3 2087.84  5012.1 2087.84  5012.4 2088.34
  5031.5 2090.45  5070.5 2092.29  5075.6 2093.88  5081.9 2094.70  5112.6 2096.44
  5119.7 2098.78  5124.8 2096.57  5143.2 2097.43  5163.7 2099.71  5169.0 2101.21
  5204.6 2104.92  5218.2 2107.54  5235.3 2112.26  5255.8 2118.31  5261.6 2121.08
#Mann=4,-1,0
  4802.7    0.16       0  4959.0    0.07       0  5008.0    0.07       0
  5012.4    0.07       0
Bank Sta=5008,5012.4
Exp/Cntr=0.3,0.1

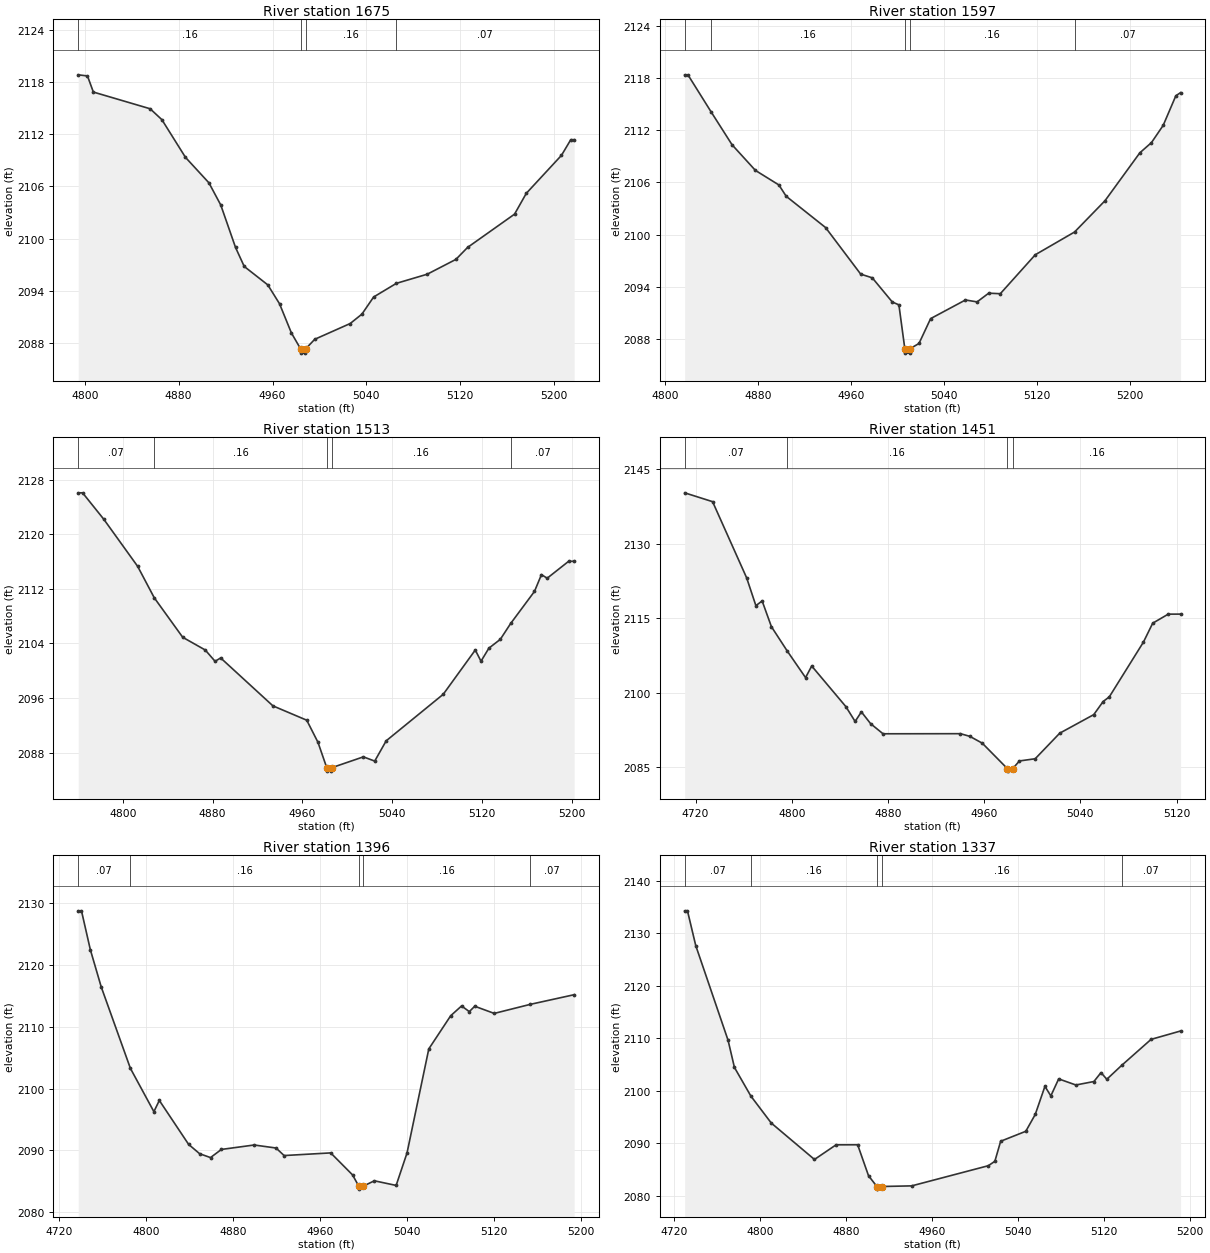
Type RM Length L Ch R = 1,1675,78,78,78
BEGIN DESCRIPTION:
Elm 76 1675.45
END DESCRIPTION:
XS GIS Cut Line= 3
      1531193.93      6763572.21      1531399.62      6763589.13
      1531615.74      6763598.25
#Sta/Elev= 30
  4794.4 2118.81  4802.3 2118.68  4807.3 2116.83  4855.7 2114.91  4865.7 2113.66
  4885.8 2109.33  4905.8 2106.40  4915.9 2103.85  4928.5 2098.97  4935.9 2096.79
  4956.0 2094.67  4966.0 2092.50  4976.1 2089.15  4983.9 2087.33  4984.2 2086.83
  4988.0 2086.83  4988.3 2087.33  4996.0 2088.42  5026.2 2090.23  5036.2 2091.31
  5046.2 2093.28  5065.6 2094.85  5091.9 2095.90  5116.3 2097.60  5126.3 2098.98
  5166.3 2102.80  5176.3 2105.19  5206.3 2109.56  5214.2 2111.35  5217.1 2111.35
#Mann=4,-1,0
  4794.4    0.16       0  4983.9    0.07       0  4988.3    0.16       0
  5065.6    0.07       0
Bank Sta=4983.9,4988.3
Exp/Cntr=0.3,0.1

Type RM Length L Ch R = 1,1597,84,84,84
BEGIN DESCRIPTION:
Elm 76 1597.08
END DESCRIPTION:
XS GIS Cut Line= 3
      1531174.41      6763633.41      1531354.05      6763652.94
      1531600.03      6763663.35
#Sta/Elev= 30
  4816.7 2118.34  4819.5 2118.34  4839.3 2114.12  4857.5 2110.31  4877.6 2107.37
  4897.8 2105.70  4904.1 2104.40  4938.0 2100.81  4968.2 2095.47  4978.2 2095.04
  4995.4 2092.27  5001.1 2091.94  5006.2 2086.90  5006.5 2086.40  5010.3 2086.40
  5010.6 2086.90  5018.4 2087.51  5028.4 2090.36  5058.4 2092.50  5068.4 2092.28
  5078.4 2093.28  5088.4 2093.22  5118.5 2097.69  5152.3 2100.30  5178.5 2103.89
  5208.5 2109.39  5218.5 2110.56  5228.6 2112.54  5239.5 2115.94  5243.6 2116.30
#Mann=5,-1,0
  4816.7    0.07       0  4839.3    0.16       0  5006.2    0.07       0
  5010.6    0.16       0  5152.3    0.07       0
Bank Sta=5006.2,5010.6
Exp/Cntr=0.3,0.1

Type RM Length L Ch R = 1,1513,62,62,62
BEGIN DESCRIPTION:
Elm 76 1513.36
END DESCRIPTION:
XS GIS Cut Line= 3
      1531152.25      6763742.78      1531385.30      6763724.55
      1531589.71      6763688.10
#Sta/Elev= 30
  4760.4 2126.05  4764.3 2126.05  4783.2 2122.17  4813.3 2115.28  4828.1 2110.67
  4853.4 2104.89  4873.5 2103.02  4882.2 2101.37  4887.2 2101.86  4933.7 2094.84
  4963.8 2092.74  4973.8 2089.50  4981.6 2085.78  4981.9 2085.28  4985.7 2085.28
  4986.0 2085.78  5014.2 2087.37  5024.3 2086.75  5034.5 2089.72  5085.3 2096.54
  5113.8 2103.02  5118.9 2101.38  5125.9 2103.29  5136.1 2104.59  5145.3 2106.91
  5166.5 2111.61  5172.7 2114.07  5177.8 2113.54  5196.9 2116.02  5201.8 2116.02
#Mann=5,-1,0
  4760.4    0.07       0  4828.1    0.16       0  4981.6    0.07       0
  4986.0    0.16       0  5145.3    0.07       0
Bank Sta=4981.6,4986
Exp/Cntr=0.3,0.1

Type RM Length L Ch R = 1,1451,55,55,55
BEGIN DESCRIPTION:
Elm 76 1450.65
END DESCRIPTION:
XS GIS Cut Line= 3
      1531155.01      6763838.00      1531435.38      6763767.88
      1531555.00      6763738.00
#Sta/Elev= 30
  4711.0 2140.25  4734.2 2138.47  4762.5 2123.14  4770.2 2117.53  4775.4 2118.48
  4783.1 2113.30  4796.2 2108.42  4811.5 2103.04  4816.6 2105.38  4845.0 2097.20
  4852.7 2094.21  4857.9 2096.14  4865.6 2093.76  4875.9 2091.73  4940.3 2091.75
  4948.1 2091.21  4958.4 2089.84  4979.3 2084.71  4979.6 2084.21  4983.7 2084.71
  4989.3 2086.26  5002.4 2086.70  5022.8 2091.85  5051.1 2095.59  5058.9 2098.23
  5064.0 2099.16  5092.4 2110.20  5100.1 2114.00  5113.0 2115.82  5123.3 2115.83
#Mann=4,-1,0
  4711.0    0.07       0  4796.2    0.16       0  4979.3    0.07       0
  4983.7    0.16       0
Bank Sta=4979.3,4983.7
Exp/Cntr=0.3,0.1

Type RM Length L Ch R = 1,1396,59,59,59
BEGIN DESCRIPTION:
Elm 76 1395.89
END DESCRIPTION:
XS GIS Cut Line= 3
      1531193.94      6763839.13      1531455.61      6763817.00
      1531648.35      6763809.19
#Sta/Elev= 30
  4737.9 2128.81  4740.9 2128.81  4749.0 2122.54  4759.0 2116.50  4785.8 2103.30
  4807.4 2096.27  4812.4 2098.09  4839.3 2090.97  4849.4 2089.46  4859.4 2088.83
  4869.4 2090.15  4899.5 2090.87  4919.6 2090.38  4927.0 2089.16  4969.8 2089.59
  4989.9 2086.02  4995.5 2084.22  4995.8 2083.72  4999.9 2084.22  5009.9 2085.07
  5029.9 2084.32  5039.9 2089.58  5059.9 2106.44  5080.0 2111.81  5090.0 2113.40
  5097.1 2112.48  5102.1 2113.35  5120.0 2112.19  5153.2 2113.66  5193.4 2115.22
#Mann=5,-1,0
  4737.9    0.07       0  4785.8    0.16       0  4995.5    0.07       0
  4999.9    0.16       0  5153.2    0.07       0
Bank Sta=4995.5,4999.9
Exp/Cntr=0.3,0.1

Type RM Length L Ch R = 1,1337,162,162,162
BEGIN DESCRIPTION:
Elm 76 1337.31
END DESCRIPTION:
XS GIS Cut Line= 3
      1531184.78      6763848.25      1531454.31      6763875.59
      1531628.83      6763952.43
#Sta/Elev= 30
  4729.8 2134.29  4732.4 2134.29  4740.1 2127.67  4770.2 2109.62  4776.1 2104.46
  4791.4 2099.00  4810.4 2093.86  4850.6 2086.92  4870.7 2089.71  4890.8 2089.72
  4900.9 2083.83  4908.7 2081.77  4909.0 2081.27  4913.1 2081.77  4941.1 2081.89
  5012.4 2085.73  5018.5 2086.57  5023.9 2090.39  5047.3 2092.29  5056.1 2095.50
  5065.1 2100.85  5070.6 2099.03  5077.9 2102.27  5093.9 2101.11  5110.7 2101.77
  5117.3 2103.47  5122.7 2102.20  5136.5 2104.84  5163.9 2109.80  5191.4 2111.40
#Mann=5,-1,0
  4729.8    0.07       0  4791.4    0.16       0  4908.7    0.07       0
  4913.1    0.16       0  5136.5    0.07       0
Bank Sta=4908.7,4913.1
Exp/Cntr=0.3,0.1

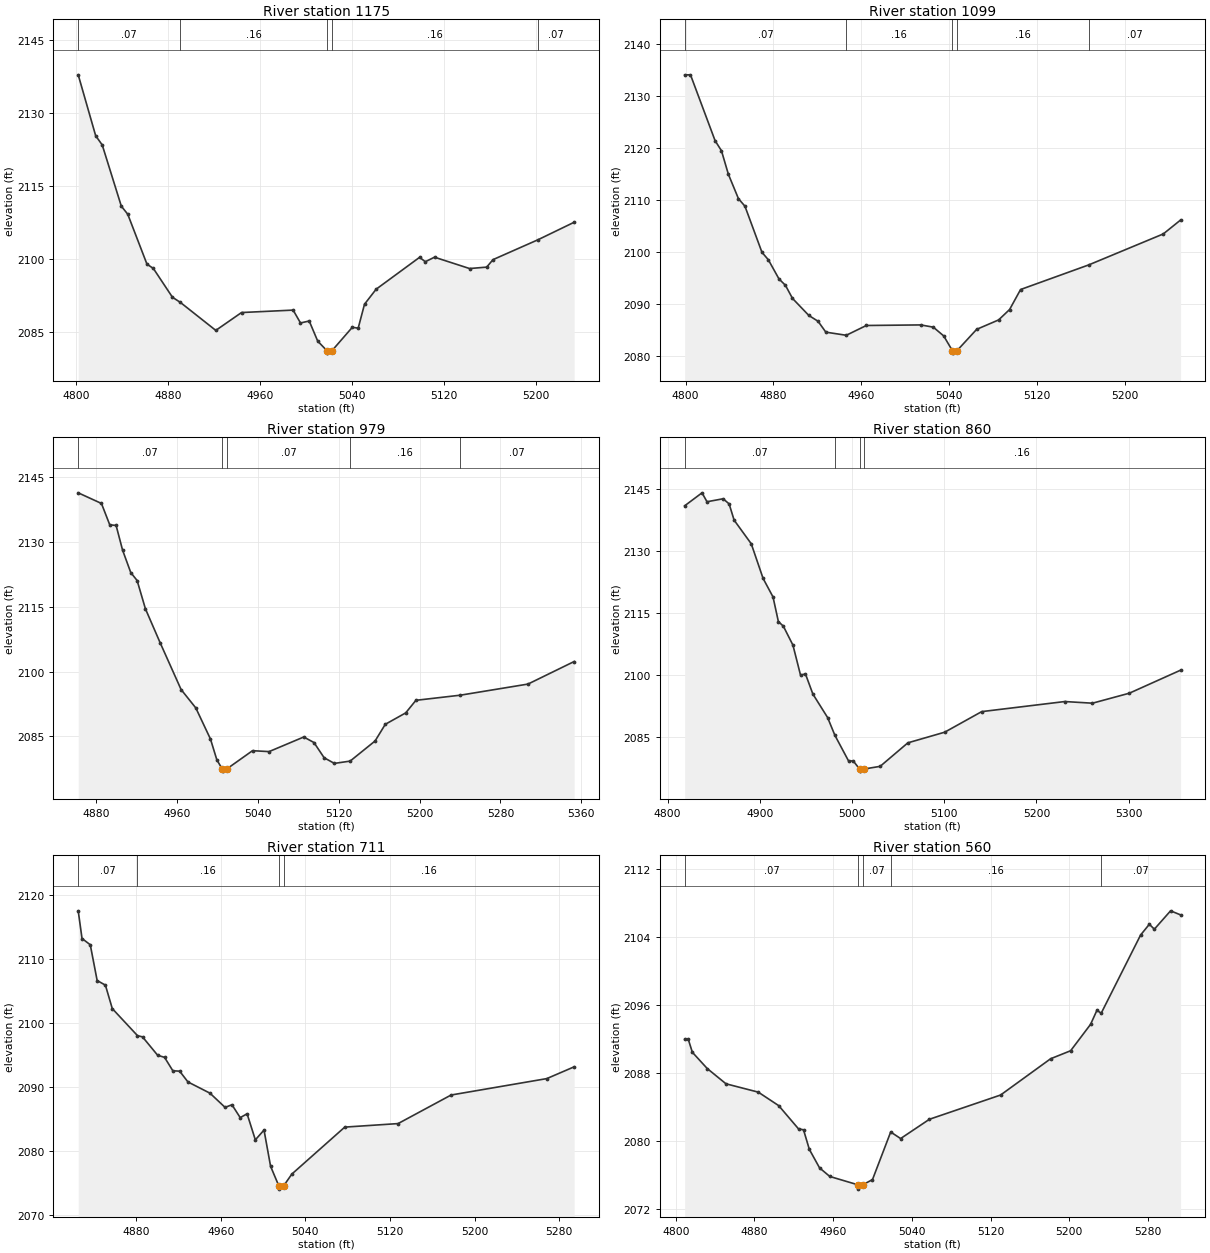
Type RM Length L Ch R = 1,1175,76,76,76
BEGIN DESCRIPTION:
Elm 76 1175.13
END DESCRIPTION:
XS GIS Cut Line= 3
      1531178.25      6763865.17      1531355.35      6763955.02
      1531584.50      6763996.68
#Sta/Elev= 30
  4801.9 2137.80  4817.1 2125.28  4822.8 2123.39  4839.4 2110.82  4845.0 2109.16
  4861.7 2098.91  4867.3 2098.01  4883.9 2092.10  4890.8 2091.04  4921.6 2085.29
  4944.0 2088.96  4988.9 2089.46  4995.3 2086.82  5002.9 2087.22  5010.3 2083.08
  5018.3 2081.12  5018.6 2080.62  5022.7 2081.12  5040.4 2085.93  5045.5 2085.75
  5051.0 2090.67  5061.1 2093.75  5098.9 2100.30  5103.9 2099.40  5111.9 2100.33
  5142.4 2098.00  5157.3 2098.29  5162.8 2099.83  5201.9 2103.91  5233.4 2107.51
#Mann=5,-1,0
  4801.9    0.07       0  4890.8    0.16       0  5018.3    0.07       0
  5022.7    0.16       0  5201.9    0.07       0
Bank Sta=5018.3,5022.7
Exp/Cntr=0.3,0.1

Type RM Length L Ch R = 1,1099,120,120,120
BEGIN DESCRIPTION:
Elm 76 1099.1
END DESCRIPTION:
XS GIS Cut Line= 3
      1531150.90      6763915.94      1531341.03      6764030.54
      1531570.78      6764035.73
#Sta/Elev= 30
  4799.1 2134.06  4804.4 2134.06  4826.8 2121.41  4832.6 2119.48  4838.9 2114.96
  4848.1 2110.26  4854.0 2108.82  4869.5 2099.96  4875.3 2098.53  4885.0 2094.85
  4890.9 2093.62  4897.3 2091.11  4912.2 2087.83  4920.6 2086.71  4927.7 2084.62
  4946.3 2084.02  4964.6 2085.90  5014.1 2086.01  5025.6 2085.58  5035.1 2083.89
  5042.9 2081.09  5043.2 2080.59  5047.3 2081.09  5065.1 2085.16  5085.1 2086.97
  5095.1 2088.97  5105.1 2092.81  5167.2 2097.54  5235.1 2103.49  5250.9 2106.17
#Mann=5,-1,0
  4799.1    0.07       0  4946.3    0.16       0  5042.9    0.07       0
  5047.3    0.16       0  5167.2    0.07       0
Bank Sta=5042.9,5047.3
Exp/Cntr=0.3,0.1

Type RM Length L Ch R = 1,979,119,119,119
BEGIN DESCRIPTION:
Elm 76 978.72
END DESCRIPTION:
XS GIS Cut Line= 3
      1531100.17      6763960.25      1531245.98      6764072.21
      1531550.29      6764112.52
#Sta/Elev= 30
  4862.1 2141.36  4885.1 2138.90  4893.3 2133.96  4899.6 2133.81  4906.0 2128.10
  4914.1 2122.91  4920.4 2121.06  4928.6 2114.52  4943.1 2106.70  4963.9 2095.83
  4978.5 2091.56  4993.0 2084.36  4999.3 2079.55  5004.6 2077.44  5005.0 2076.94
  5009.1 2077.44  5034.6 2081.67  5051.0 2081.46  5085.3 2084.84  5095.4 2083.56
  5105.5 2080.03  5115.6 2078.73  5131.2 2079.26  5155.9 2083.92  5166.0 2087.78
  5186.2 2090.42  5196.3 2093.33  5240.3 2094.52  5307.2 2097.09  5352.9 2102.31
#Mann=5,-1,0
  4862.1    0.07       0  5004.6    0.07       0  5009.1    0.07       0
  5131.2    0.16       0  5240.3    0.07       0
Bank Sta=5004.6,5009.1
Exp/Cntr=0.3,0.1

Type RM Length L Ch R = 1,860,149,149,149
BEGIN DESCRIPTION:
Elm 76 859.97
END DESCRIPTION:
XS GIS Cut Line= 3
      1531036.37      6764094.35      1531201.71      6764162.05
      1531560.51      6764177.65
#Sta/Elev= 30
  4818.6 2141.00  4837.4 2144.14  4842.8 2141.98  4860.3 2142.70  4866.8 2141.46
  4872.2 2137.53  4890.8 2131.80  4903.6 2123.43  4914.4 2118.92  4920.2 2112.97
  4925.6 2111.85  4936.0 2107.26  4944.2 2100.02  4949.6 2100.27  4957.6 2095.42
  4973.6 2089.72  4981.5 2085.42  4996.3 2079.22  5001.4 2079.22  5008.3 2077.25
  5008.7 2076.75  5012.8 2077.25  5030.6 2077.91  5060.6 2083.60  5100.6 2086.18
  5140.7 2091.16  5230.8 2093.60  5260.8 2093.20  5300.8 2095.62  5356.4 2101.20
#Mann=4,-1,0
  4818.6    0.07       0  4981.5    0.16       0  5008.3    0.07       0
  5012.8    0.16       0
Bank Sta=5008.3,5012.8
Exp/Cntr=0.3,0.1

Type RM Length L Ch R = 1,711,151,151,151
BEGIN DESCRIPTION:
Elm 76 711.29
END DESCRIPTION:
XS GIS Cut Line= 3
      1531024.62      6764182.88      1531158.74      6764296.17
      1531450.84      6764320.83
#Sta/Elev= 30
  4825.4 2117.48  4829.0 2113.16  4836.8 2112.18  4843.3 2106.60  4851.1 2105.88
  4857.6 2102.22  4881.4 2098.00  4886.2 2097.80  4900.5 2094.93  4907.0 2094.61
  4914.8 2092.52  4921.3 2092.45  4929.1 2090.77  4949.9 2089.02  4964.2 2086.80
  4970.7 2087.21  4978.5 2085.20  4985.0 2085.80  4992.8 2081.73  5001.0 2083.26
  5007.2 2077.61  5015.0 2074.54  5015.3 2074.04  5019.5 2074.54  5027.3 2076.39
  5077.3 2083.72  5127.7 2084.27  5177.8 2088.73  5268.2 2091.29  5294.1 2093.13
#Mann=4,-1,0
  4825.4    0.07       0  4881.4    0.16       0  5015.0    0.07       0
  5019.5    0.16       0
Bank Sta=5015,5019.5
Exp/Cntr=0.3,0.1

Type RM Length L Ch R = 1,560,72,72,72
BEGIN DESCRIPTION:
Elm 76 560.409
END DESCRIPTION:
XS GIS Cut Line= 3
      1531012.94      6764380.81      1531196.86      6764431.94
      1531505.00      6764488.00
#Sta/Elev= 30
  4809.1 2091.95  4812.8 2091.95  4816.9 2090.44  4832.0 2088.53  4851.1 2086.73
  4883.9 2085.75  4904.7 2084.16  4924.8 2081.43  4929.9 2081.32  4935.8 2079.02
  4946.2 2076.84  4956.6 2075.83  4985.4 2074.84  4985.7 2074.34  4989.9 2074.84
  5000.0 2075.46  5018.5 2081.06  5028.6 2080.29  5057.9 2082.56  5130.2 2085.41
  5181.1 2089.68  5201.4 2090.62  5221.7 2093.73  5228.1 2095.37  5232.5 2095.04
  5272.5 2104.23  5281.4 2105.50  5286.5 2104.92  5303.0 2107.08  5313.2 2106.60
#Mann=5,-1,0
  4809.1    0.07       0  4985.4    0.07       0  4989.9    0.07       0
  5018.5    0.16       0  5232.5    0.07       0
Bank Sta=4985.4,4989.9
Exp/Cntr=0.3,0.1

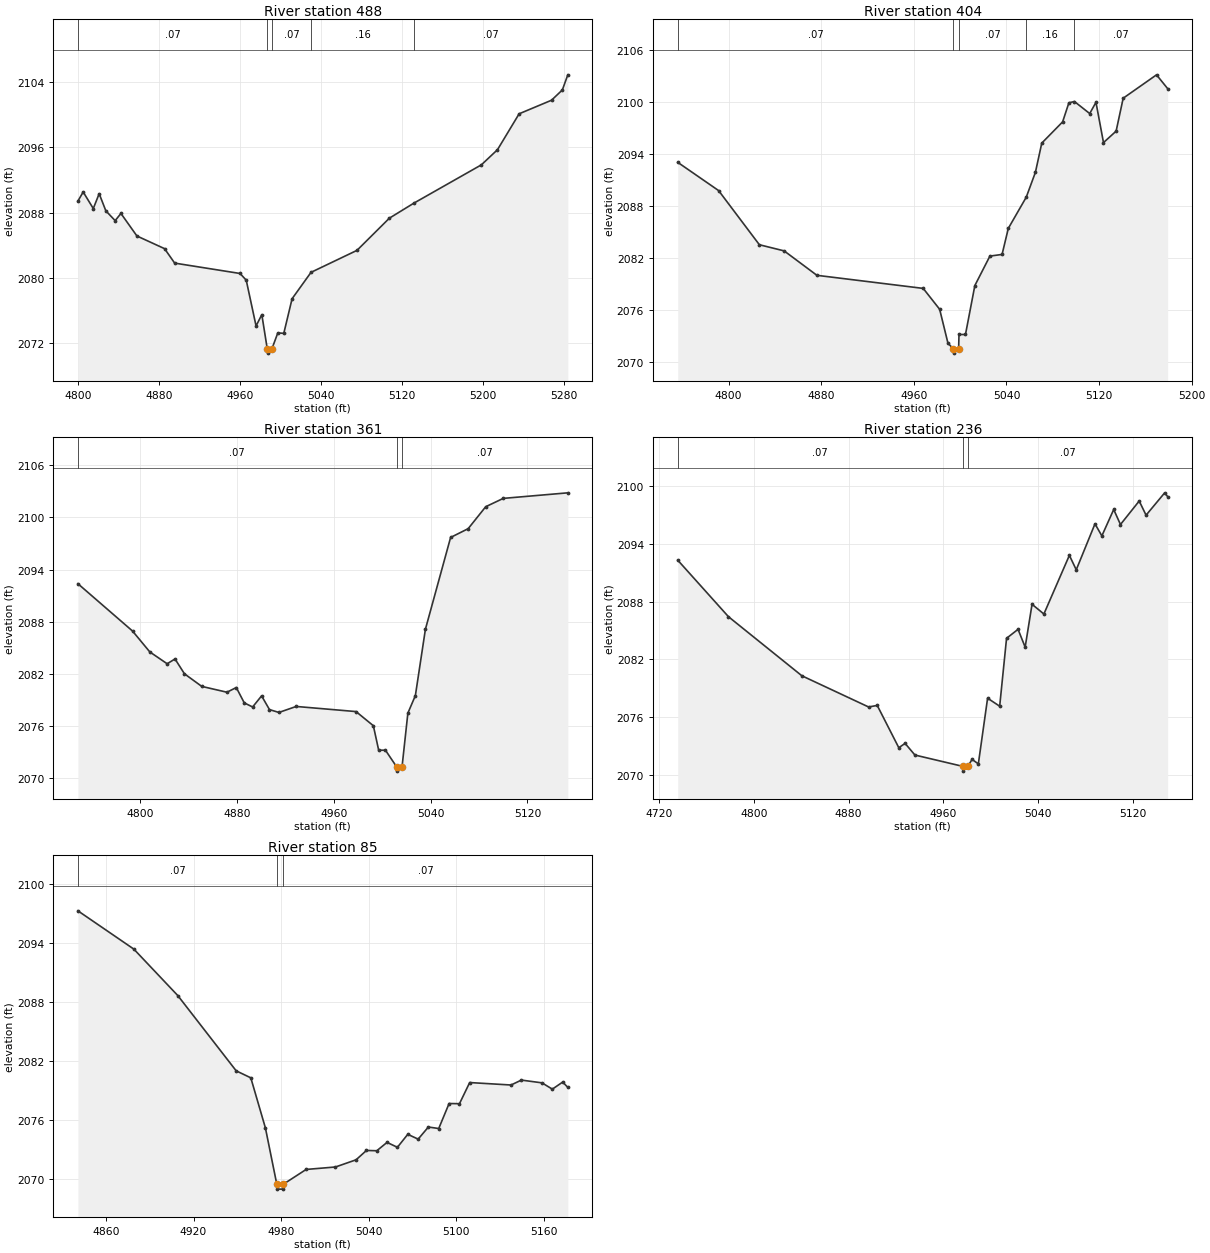
Type RM Length L Ch R = 1,488,84,84,84
BEGIN DESCRIPTION:
Elm 76 4380
END DESCRIPTION:
XS GIS Cut Line= 3
      1531031.09      6764402.91      1531204.63      6764503.34
      1531470.03      6764603.00
#Sta/Elev= 30
  4799.5 2089.40  4804.7 2090.52  4814.7 2088.49  4820.5 2090.31  4827.1 2088.21
  4836.3 2087.01  4842.0 2087.89  4857.8 2085.13  4885.1 2083.58  4895.1 2081.81
  4959.7 2080.54  4965.8 2079.72  4975.5 2074.12  4981.2 2075.50  4986.6 2071.29
  4986.9 2070.79  4991.1 2071.29  4997.0 2073.27  5002.9 2073.21  5011.1 2077.45
  5029.8 2080.68  5075.2 2083.37  5107.2 2087.31  5131.4 2089.15  5198.1 2093.84
  5214.0 2095.69  5235.4 2100.09  5267.4 2101.75  5278.1 2103.01  5283.5 2104.86
#Mann=5,-1,0
  4799.5    0.07       0  4986.6    0.07       0  4991.1    0.07       0
  5029.8    0.16       0  5131.4    0.07       0
Bank Sta=4986.6,4991.1
Exp/Cntr=0.3,0.1

Type RM Length L Ch R = 1,404,43,43,43
BEGIN DESCRIPTION:
Elm 76 4379
END DESCRIPTION:
XS GIS Cut Line= 3
      1531025.91      6764417.24      1531201.48      6764586.55
      1531365.75      6764658.14
#Sta/Elev= 30
  4756.1 2093.03  4791.4 2089.77  4826.6 2083.52  4848.0 2082.81  4876.3 2079.99
  4968.1 2078.48  4982.3 2076.07  4989.5 2072.14  4994.2 2071.51  4994.5 2071.01
  4998.7 2071.51  4999.0 2073.16  5004.6 2073.16  5012.7 2078.81  5025.7 2082.21
  5036.2 2082.40  5041.6 2085.41  5057.1 2089.01  5065.0 2091.88  5070.5 2095.25
  5088.5 2097.70  5093.9 2099.90  5098.7 2100.05  5111.9 2098.66  5117.3 2099.96
  5123.8 2095.31  5134.7 2096.63  5140.8 2100.43  5169.6 2103.13  5179.2 2101.54
#Mann=5,-1,0
  4756.1    0.07       0  4994.2    0.07       0  4998.7    0.07       0
  5057.1    0.16       0  5098.7    0.07       0
Bank Sta=4994.2,4998.7
Exp/Cntr=0.3,0.1

Type RM Length L Ch R = 1,361,125,125,125
BEGIN DESCRIPTION:
Elm 76 4378
END DESCRIPTION:
XS GIS Cut Line= 3
      1531011.63      6764427.71      1531173.73      6764619.74
      1531295.42      6764712.97
#Sta/Elev= 30
  4748.7 2092.37  4793.8 2086.92  4808.1 2084.51  4822.4 2083.15  4828.9 2083.70
  4836.7 2081.99  4851.0 2080.54  4871.8 2079.87  4879.5 2080.41  4886.1 2078.64
  4893.0 2078.17  4900.4 2079.45  4906.9 2077.87  4914.7 2077.54  4929.0 2078.23
  4978.4 2077.64  4992.7 2076.01  4997.1 2073.19  5002.7 2073.19  5011.9 2071.28
  5012.2 2070.78  5016.4 2071.28  5021.2 2077.46  5027.4 2079.48  5035.7 2087.13
  5056.5 2097.70  5071.0 2098.71  5085.5 2101.24  5100.0 2102.20  5153.3 2102.84
#Mann=3,-1,0
  4748.7    0.07       0  5011.9    0.07       0  5016.4    0.07       0
Bank Sta=5011.9,5016.4
Exp/Cntr=0.3,0.1

Type RM Length L Ch R = 1,236,151,151,151
BEGIN DESCRIPTION:
Elm 76 4376
END DESCRIPTION:
XS GIS Cut Line= 3
      1530986.86      6764439.37      1531075.21      6764688.36
      1531204.29      6764762.99
#Sta/Elev= 30
  4735.8 2092.30  4778.6 2086.43  4840.5 2080.30  4896.8 2077.06  4904.1 2077.22
  4922.3 2072.83  4927.6 2073.28  4935.9 2072.07  4976.1 2070.90  4976.4 2070.40
  4980.6 2070.90  4984.1 2071.62  4989.4 2071.15  4997.2 2077.97  5007.4 2077.14
  5013.2 2084.19  5022.9 2085.12  5028.9 2083.27  5034.7 2087.72  5044.7 2086.71
  5066.2 2092.80  5072.0 2091.30  5087.8 2096.07  5093.6 2094.82  5103.6 2097.56
  5109.3 2096.00  5125.1 2098.44  5130.9 2096.97  5146.6 2099.29  5149.1 2098.90
#Mann=3,-1,0
  4735.8    0.07       0  4976.1    0.07       0  4980.6    0.07       0
Bank Sta=4976.1,4980.6
Exp/Cntr=0.3,0.1

Type RM Length L Ch R = 1,85,0,0,0
BEGIN DESCRIPTION:
Elm 76 4375
END DESCRIPTION:
XS GIS Cut Line= 3
      1530932.17      6764479.71      1530939.97      6764638.72
      1531065.00      6764763.01
#Sta/Elev= 30
  4840.8 2097.28  4879.1 2093.39  4909.2 2088.67  4949.2 2081.02  4959.2 2080.31
  4969.2 2075.22  4977.0 2069.50  4977.3 2069.00  4981.2 2069.00  4981.5 2069.50
  4997.1 2071.00  5017.2 2071.25  5031.3 2071.98  5038.4 2072.93  5045.5 2072.90
  5052.5 2073.75  5059.6 2073.25  5066.7 2074.57  5073.8 2074.08  5080.8 2075.31
  5087.9 2075.16  5095.0 2077.70  5102.1 2077.68  5109.1 2079.83  5137.4 2079.58
  5144.5 2080.08  5158.6 2079.80  5165.7 2079.16  5172.8 2079.88  5176.3 2079.34
#Mann=3,-1,0
  4840.8    0.07       0  4977.0    0.07       0  4981.5    0.07       0
Bank Sta=4977,4981.5
Exp/Cntr=0.3,0.1

Chan Stop Cuts=-1