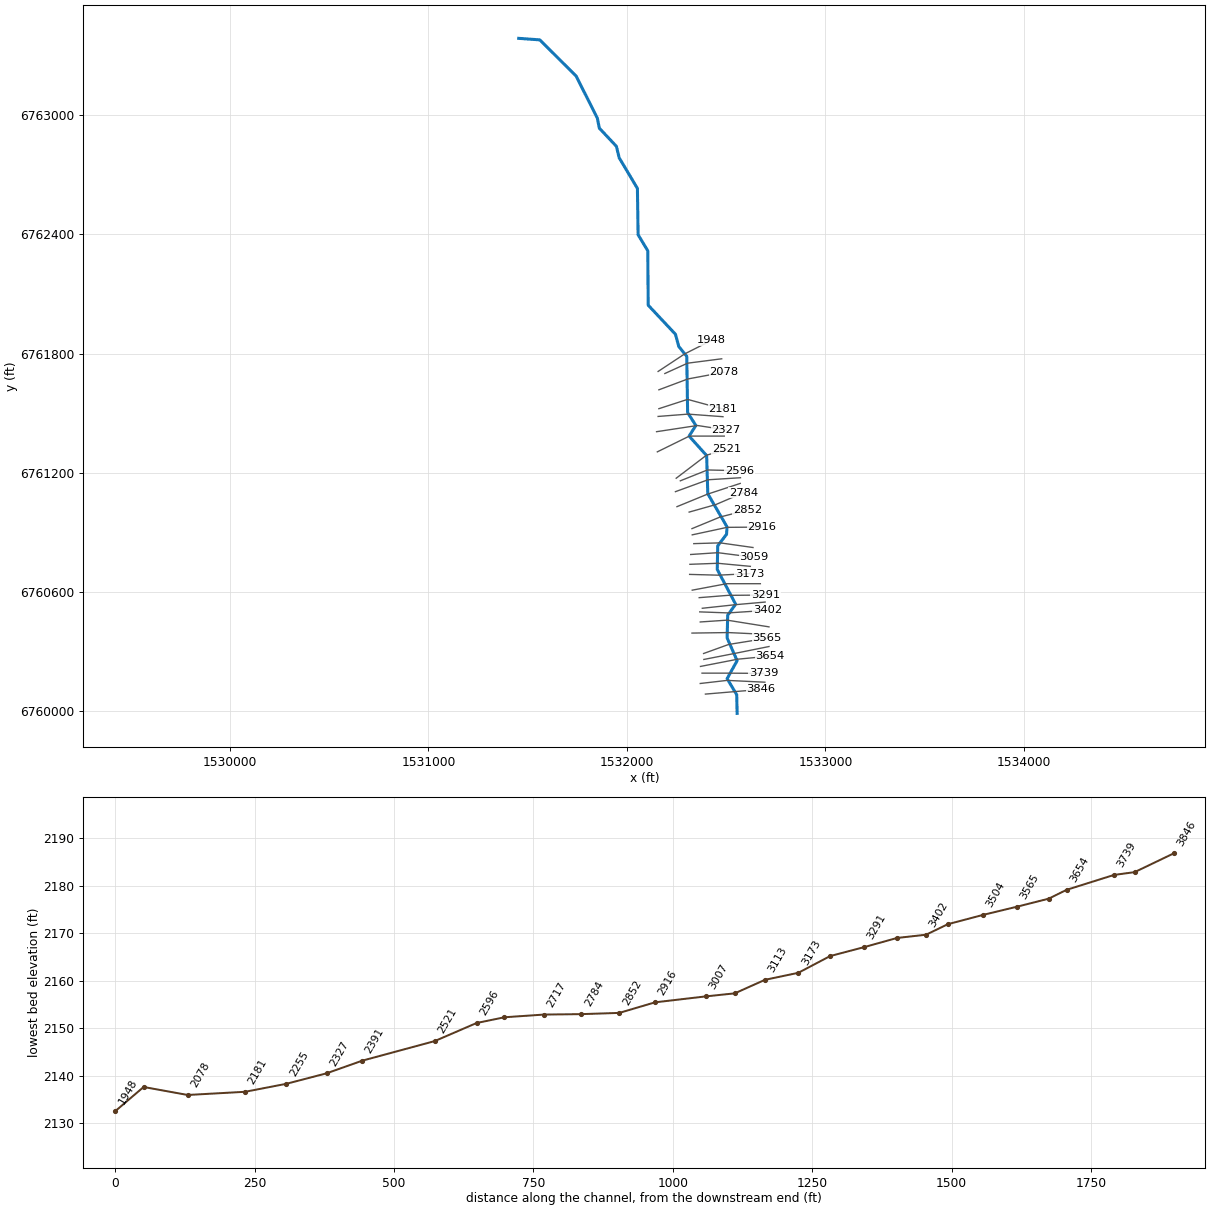
--- Elm 77.prj (project) ---

Proj Title=Elm 77 Base Level Engineering
Current Plan=p01
Default Exp/Contr=0.3,0.1
English Units
Geom File=g01
Flow File=f01
Plan File=p01
BEGIN DESCRIPTION:
Elm 77
END DESCRIPTION:

--- Elm 77.p01 (plan) ---

Plan Title=Multiple Run
Short Identifier=Multiple
Geom File=g01
Flow File=f01
Subcritical Flow
K Sum by GR= 0
Std Step Tol= 0.01
Critical Tol= 0.01
Num of Std Step Trials= 20
Max Error Tol= 0.3
Flow Tol Ratio= 0.001
Split Flow NTrial= 30
Split Flow Tol= 0.02
Split Flow Ratio= 0.02
Log Output Level= 0
Friction Slope Method= 1
Unsteady Friction Slope Method= 2
Unsteady Bridges Friction Slope Method= 1
Parabolic Critical Depth
Global Vel Dist=  1 , 1 , 1
Global Log Level= 0
CheckData=True
Encroach Param= -1, 0, 0, 0
BEGIN DESCRIPTION:
Multiple Run
END DESCRIPTION:

--- Elm 77.f01 (steady flow) ---

Flow Title=Multiple
Number of Profiles=7
Profile Names=10-year,25-year,50-year,1pct_min,100-year,1pct_plu,500-year
River Rch & RM= Elm 77,Reach-1,3846
     252     359     450     352     564     776     895
Boundary for River Rch & Prof#=Elm 77,Reach-1,1
Up Type=0
Dn Type=3
Dn Slope=0.005
Boundary for River Rch & Prof#=Elm 77,Reach-1,2
Up Type=0
Dn Type=3
Dn Slope=0.005
Boundary for River Rch & Prof#=Elm 77,Reach-1,3
Up Type=0
Dn Type=3
Dn Slope=0.005
Boundary for River Rch & Prof#=Elm 77,Reach-1,4
Up Type=0
Dn Type=3
Dn Slope=0.005
Boundary for River Rch & Prof#=Elm 77,Reach-1,5
Up Type=0
Dn Type=3
Dn Slope=0.005
Boundary for River Rch & Prof#=Elm 77,Reach-1,6
Up Type=0
Dn Type=3
Dn Slope=0.005
Boundary for River Rch & Prof#=Elm 77,Reach-1,7
Up Type=0
Dn Type=3
Dn Slope=0.005

--- Elm 77.g01 (geometry) ---

Geom Title=Existing Conditions

River Reach=Elm 77,Reach-1
Reach XY= 30
      1532555.00      6759988.00      1532552.87      6760082.14
      1532504.59      6760163.00      1532554.89      6760253.39
      1532504.62      6760367.86      1532507.45      6760482.14
      1532547.47      6760538.01      1532454.76      6760712.92
      1532457.28      6760832.07      1532501.63      6760889.74
      1532504.25      6760927.32      1532407.24      6761093.93
      1532401.44      6761286.54      1532313.01      6761384.67
      1532347.19      6761437.90      1532305.65      6761503.16
      1532301.25      6761786.45      1532261.14      6761835.83
      1532244.24      6761897.68      1532107.06      6762043.85
      1532104.93      6762317.97      1532056.22      6762398.50
      1532052.76      6762632.07      1531961.10      6762785.81
      1531946.84      6762844.05      1531860.85      6762935.71
      1531850.81      6762986.26      1531744.24      6763197.68
      1531561.22      6763380.26      1531455.00      6763388.00

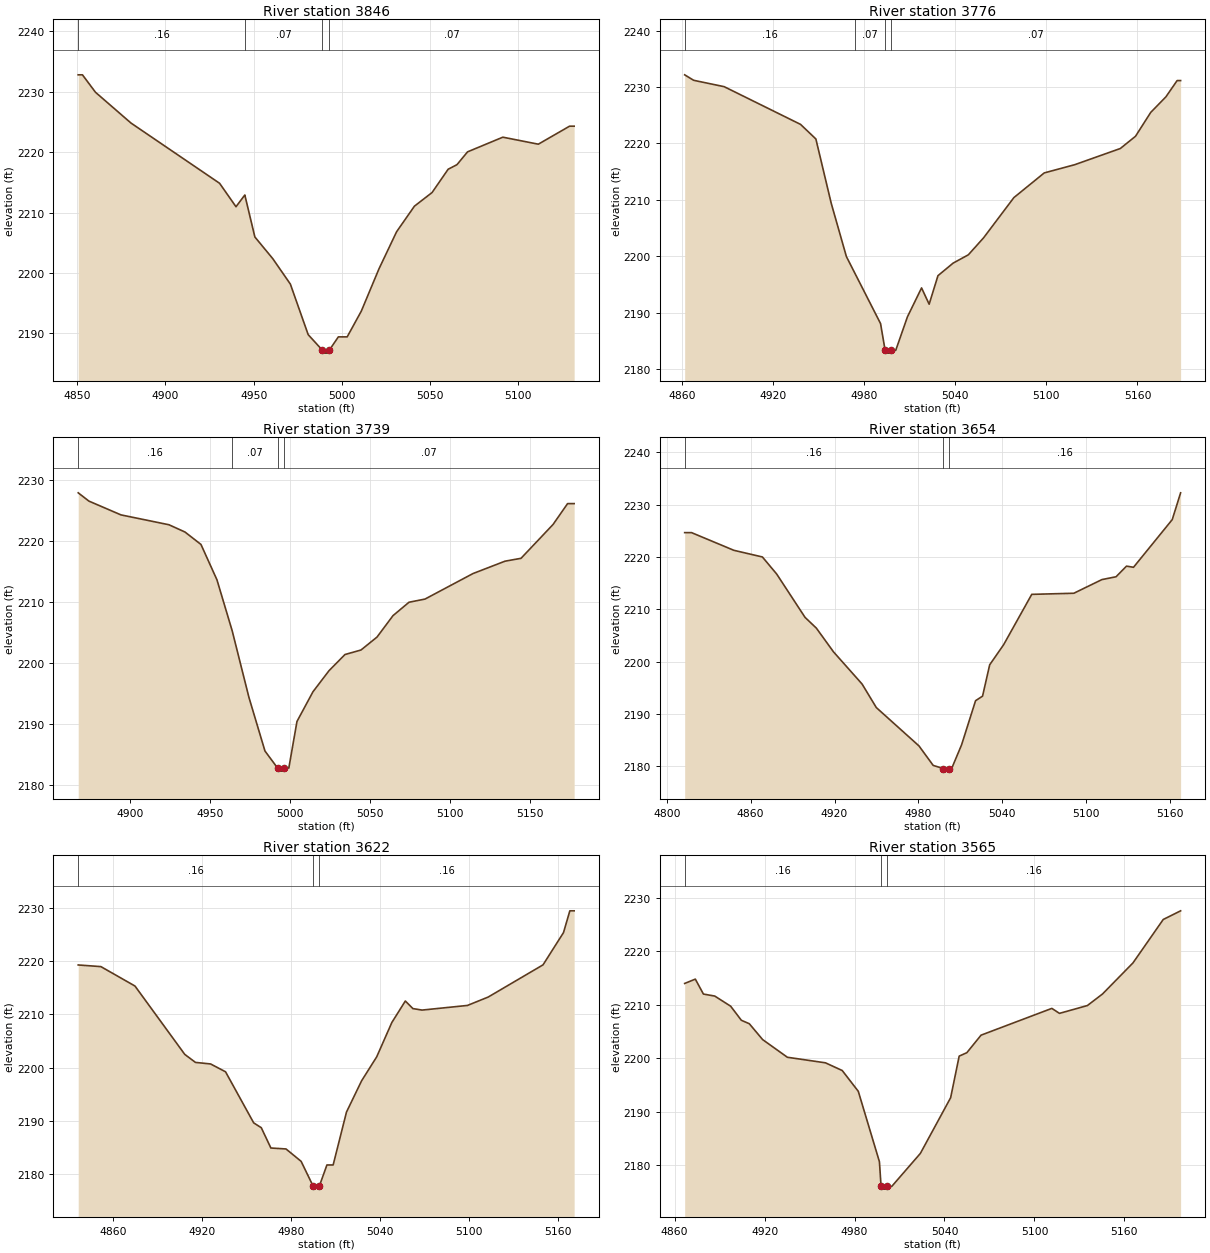
Type RM Length L Ch R = 1,3846,70,70,70
BEGIN DESCRIPTION:
Elm 77 3845.817
END DESCRIPTION:
XS GIS Cut Line= 3
      1532395.21      6760085.13      1532544.08      6760097.67
      1532675.23      6760108.58
#Sta/Elev= 30
  4850.6 2232.81  4853.0 2232.81  4860.4 2229.92  4880.5 2224.83  4930.7 2214.86
  4940.0 2210.98  4945.0 2212.92  4945.2 2212.68  4950.7 2205.97  4960.8 2202.40
  4970.8 2198.18  4980.9 2189.81  4988.9 2187.25  4989.1 2186.75  4992.6 2186.75
  4992.9 2187.25  4998.0 2189.44  5003.0 2189.44  5011.0 2193.70  5021.0 2200.69
  5031.0 2206.84  5041.1 2211.07  5051.1 2213.33  5060.2 2217.18  5065.2 2217.94
  5071.2 2220.06  5091.2 2222.49  5111.3 2221.33  5129.0 2224.31  5131.6 2224.31
#Mann=4,-1,0
  4850.6    0.16       0  4945.2    0.07       0  4988.9    0.07       0
  4992.9    0.07       0
Bank Sta=4988.9,4992.9
Exp/Cntr=0.3,0.1

Type RM Length L Ch R = 1,3776,37,37,37
BEGIN DESCRIPTION:
Elm 77 3776.24
END DESCRIPTION:
XS GIS Cut Line= 3
      1532369.18      6760138.52      1532504.61      6760154.14
      1532694.67      6760145.03
#Sta/Elev= 30
  4861.8 2232.18  4867.7 2231.21  4887.8 2230.08  4938.1 2223.39  4948.2 2220.80
  4958.3 2209.40  4968.3 2199.94  4973.8 2197.03  4990.8 2188.05  4993.8 2183.31
  4994.1 2182.81  4997.6 2182.81  4997.8 2183.31  5000.8 2183.31  5008.5 2189.25
  5017.8 2194.38  5022.8 2191.49  5028.6 2196.55  5038.6 2198.78  5048.6 2200.25
  5058.6 2203.25  5078.6 2210.40  5098.6 2214.78  5118.7 2216.24  5148.7 2219.11
  5158.7 2221.28  5168.7 2225.51  5178.7 2228.27  5186.1 2231.16  5188.4 2231.16
#Mann=4,-1,0
  4861.8    0.16       0  4973.8    0.07       0  4993.8    0.07       0
  4997.8    0.07       0
Bank Sta=4993.8,4997.8
Exp/Cntr=0.3,0.1

Type RM Length L Ch R = 1,3739,85,85,85
BEGIN DESCRIPTION:
Elm 77 3738.75
END DESCRIPTION:
XS GIS Cut Line= 3
      1532378.26      6760190.60      1532509.82      6760190.60
      1532688.16      6760189.30
#Sta/Elev= 30
  4867.5 2227.90  4874.2 2226.54  4894.2 2224.28  4924.2 2222.66  4934.2 2221.47
  4944.2 2219.43  4954.2 2213.62  4963.7 2205.27  4974.2 2194.31  4984.2 2185.52
  4992.1 2182.72  4992.4 2182.22  4995.9 2182.22  4996.1 2182.72  4999.1 2182.72
  5004.2 2190.37  5014.2 2195.25  5024.2 2198.70  5034.2 2201.36  5044.2 2202.10
  5054.2 2204.22  5064.2 2207.74  5074.2 2209.94  5084.2 2210.46  5114.2 2214.65
  5134.2 2216.68  5144.2 2217.15  5164.2 2222.70  5173.3 2226.13  5177.4 2226.13
#Mann=4,-1,0
  4867.5    0.16       0  4963.7    0.07       0  4992.1    0.07       0
  4996.1    0.07       0
Bank Sta=4992.1,4996.1
Exp/Cntr=0.3,0.1

Type RM Length L Ch R = 1,3654,32,32,32
BEGIN DESCRIPTION:
Elm 77 3654.08
END DESCRIPTION:
XS GIS Cut Line= 3
      1532370.46      6760224.45      1532557.99      6760260.92
      1532721.01      6760276.44
#Sta/Elev= 30
  4812.8 2224.64  4817.7 2224.64  4848.0 2221.26  4868.4 2219.99  4878.6 2216.74
  4898.9 2208.46  4907.0 2206.40  4919.3 2201.86  4939.7 2195.73  4949.9 2191.23
  4980.4 2183.91  4990.6 2180.18  4997.8 2179.59  4998.0 2179.09  5001.5 2179.09
  5001.8 2179.59  5003.8 2179.59  5010.9 2184.11  5020.9 2192.54  5025.9 2193.41
  5031.0 2199.39  5041.0 2203.24  5061.1 2212.85  5091.2 2213.06  5111.3 2215.67
  5121.4 2216.21  5128.9 2218.24  5133.9 2218.02  5161.6 2227.12  5167.6 2232.24
#Mann=3,-1,0
  4812.8    0.16       0  4997.8    0.07       0  5001.8    0.16       0
Bank Sta=4997.8,5001.8
Exp/Cntr=0.3,0.1

Type RM Length L Ch R = 1,3622,57,57,57
BEGIN DESCRIPTION:
Elm 77 3621.81
END DESCRIPTION:
XS GIS Cut Line= 3
      1532387.39      6760259.61      1532554.09      6760292.17
      1532715.60      6760324.73
#Sta/Elev= 30
  4836.6 2219.26  4851.9 2218.95  4874.9 2215.31  4908.5 2202.49  4915.7 2200.99
  4925.9 2200.70  4936.0 2199.23  4955.0 2189.65  4960.1 2188.75  4966.6 2184.94
  4976.8 2184.76  4987.0 2182.44  4995.2 2177.73  4995.4 2177.23  4999.2 2177.73
  5004.4 2181.76  5008.6 2181.76  5017.6 2191.68  5027.8 2197.54  5038.0 2202.04
  5048.2 2208.47  5057.3 2212.50  5062.4 2211.08  5068.6 2210.80  5099.2 2211.67
  5113.2 2213.24  5150.2 2219.28  5164.0 2225.32  5168.3 2229.41  5171.2 2229.41
#Mann=3,-1,0
  4836.6    0.16       0  4995.2    0.07       0  4999.2    0.16       0
Bank Sta=4995.2,4999.2
Exp/Cntr=0.3,0.1

Type RM Length L Ch R = 1,3565,61,61,61
BEGIN DESCRIPTION:
Elm 77 3564.88
END DESCRIPTION:
XS GIS Cut Line= 3
      1532386.10      6760289.55      1532512.42      6760335.13
      1532706.43      6760366.38
#Sta/Elev= 30
  4866.7 2213.97  4873.8 2214.78  4879.2 2211.99  4886.8 2211.61  4897.4 2209.71
  4904.5 2207.09  4909.8 2206.45  4918.7 2203.48  4935.2 2200.18  4960.6 2199.14
  4971.8 2197.70  4982.5 2193.82  4996.6 2180.66  4997.7 2176.04  4998.0 2175.54
  5001.5 2175.54  5001.7 2176.04  5004.8 2176.04  5023.9 2182.21  5044.1 2192.62
  5049.8 2200.39  5054.9 2201.03  5064.4 2204.31  5111.6 2209.31  5116.7 2208.38
  5135.3 2209.84  5145.4 2212.00  5165.7 2217.80  5185.9 2225.92  5197.5 2227.54
#Mann=3,-1,0
  4866.7    0.16       0  4997.7    0.07       0  5001.7    0.16       0
Bank Sta=4997.7,5001.7
Exp/Cntr=0.3,0.1

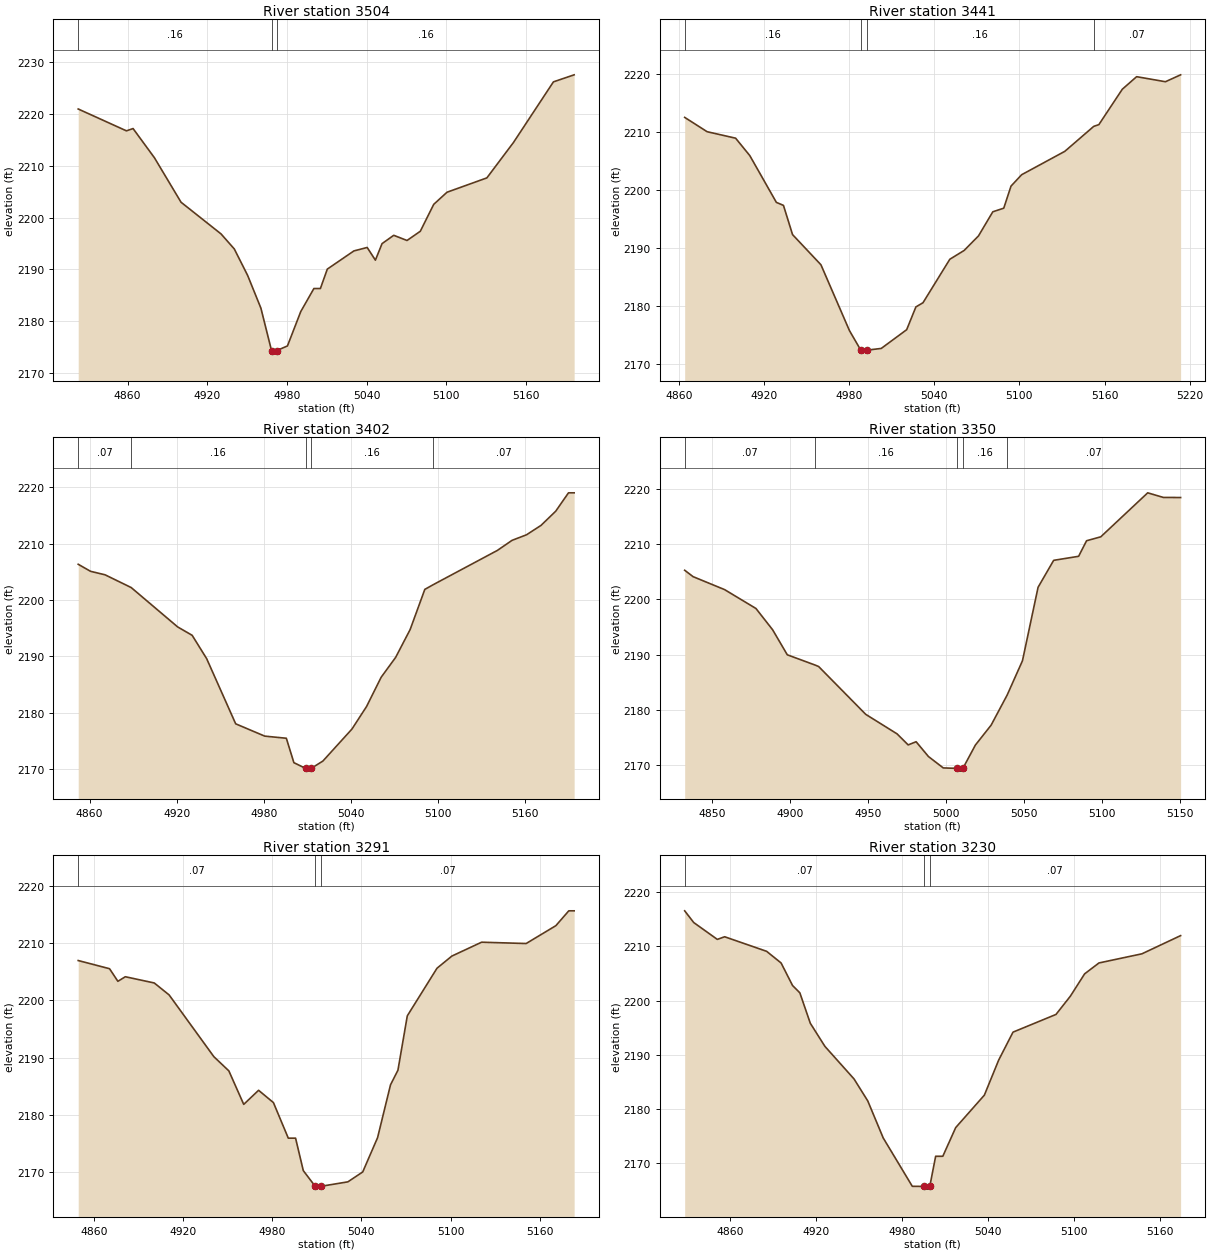
Type RM Length L Ch R = 1,3504,63,63,63
BEGIN DESCRIPTION:
Elm 77 3503.62
END DESCRIPTION:
XS GIS Cut Line= 3
      1532327.56      6760392.43      1532509.82      6760395.03
      1532700.62      6760385.94
#Sta/Elev= 30
  4822.9 2220.97  4859.2 2216.75  4864.2 2217.19  4880.3 2211.54  4900.3 2202.96
  4930.4 2196.84  4940.4 2193.93  4950.4 2188.84  4960.4 2182.51  4968.4 2174.31
  4968.6 2173.81  4972.4 2174.31  4980.4 2175.20  4990.4 2181.83  5000.3 2186.29
  5005.2 2186.29  5010.4 2190.04  5030.4 2193.55  5040.4 2194.22  5046.6 2191.77
  5051.6 2194.96  5060.4 2196.57  5070.4 2195.57  5080.4 2197.35  5090.5 2202.55
  5100.5 2204.89  5130.5 2207.66  5150.5 2214.49  5180.6 2226.21  5196.2 2227.57
#Mann=3,-1,0
  4822.9    0.16       0  4968.4    0.07       0  4972.4    0.16       0
Bank Sta=4968.4,4972.4
Exp/Cntr=0.3,0.1

Type RM Length L Ch R = 1,3441,39,39,39
BEGIN DESCRIPTION:
Elm 77 3441.06
END DESCRIPTION:
XS GIS Cut Line= 3
      1532369.19      6760448.42      1532504.61      6760457.53
      1532715.59      6760423.67
#Sta/Elev= 30
  4864.2 2212.52  4880.0 2210.05  4900.1 2208.93  4910.1 2205.92  4928.8 2197.86
  4933.8 2197.34  4940.2 2192.30  4960.2 2187.10  4980.3 2175.74  4988.3 2172.36
  4988.5 2171.86  4992.3 2172.36  5002.7 2172.67  5020.6 2175.90  5027.1 2179.83
  5032.1 2180.55  5051.0 2188.05  5061.1 2189.57  5071.2 2192.08  5081.3 2196.24
  5089.0 2196.86  5094.1 2200.66  5101.6 2202.63  5132.0 2206.66  5152.4 2210.97
  5156.0 2211.27  5172.5 2217.37  5182.6 2219.54  5202.9 2218.67  5213.6 2219.86
#Mann=4,-1,0
  4864.2    0.16       0  4988.3    0.07       0  4992.3    0.16       0
  5152.4    0.07       0
Bank Sta=4988.3,4992.3
Exp/Cntr=0.3,0.1

Type RM Length L Ch R = 1,3402,52,52,52
BEGIN DESCRIPTION:
Elm 77 3402.37
END DESCRIPTION:
XS GIS Cut Line= 3
      1532366.54      6760499.20      1532509.82      6760493.99
      1532707.72      6760507.01
#Sta/Elev= 30
  4852.2 2206.34  4860.7 2205.09  4870.7 2204.47  4888.7 2202.21  4920.7 2195.23
  4930.7 2193.74  4940.7 2189.60  4960.7 2178.04  4980.7 2175.86  4995.6 2175.48
  5000.8 2171.15  5008.8 2170.15  5009.0 2169.65  5012.5 2169.65  5012.8 2170.15
  5020.8 2171.44  5040.8 2177.11  5050.9 2181.12  5060.9 2186.29  5070.9 2189.82
  5080.9 2194.76  5091.0 2201.88  5096.6 2202.69  5141.1 2208.81  5151.1 2210.58
  5161.1 2211.57  5171.1 2213.24  5181.2 2215.75  5190.0 2219.01  5193.9 2219.01
#Mann=5,-1,0
  4852.2    0.07       0  4888.7    0.16       0  5008.8    0.07       0
  5012.8    0.16       0  5096.6    0.07       0
Bank Sta=5008.8,5012.8
Exp/Cntr=0.3,0.1

Type RM Length L Ch R = 1,3350,59,59,59
BEGIN DESCRIPTION:
Elm 77 3349.69
END DESCRIPTION:
XS GIS Cut Line= 3
      1532379.59      6760517.42      1532548.88      6760535.66
      1532696.04      6760548.68
#Sta/Elev= 30
  4832.2 2205.27  4837.6 2204.11  4857.8 2201.77  4877.9 2198.36  4888.6 2194.51
  4898.0 2189.99  4915.9 2188.13  4918.1 2187.87  4948.3 2179.23  4968.4 2175.70
  4975.5 2173.71  4980.6 2174.28  4988.5 2171.61  4998.0 2169.55  5006.6 2169.47
  5006.9 2168.97  5010.4 2168.97  5010.6 2169.47  5018.6 2173.68  5028.7 2177.28
  5039.0 2182.73  5048.8 2188.92  5058.8 2202.19  5068.8 2207.06  5084.8 2207.79
  5089.9 2210.60  5099.0 2211.31  5129.1 2219.26  5139.1 2218.43  5150.2 2218.41
#Mann=5,-1,0
  4832.2    0.07       0  4915.9    0.16       0  5006.6    0.07       0
  5010.6    0.16       0  5039.0    0.07       0
Bank Sta=5006.6,5010.6
Exp/Cntr=0.3,0.1

Type RM Length L Ch R = 1,3291,61,61,61
BEGIN DESCRIPTION:
Elm 77 3290.83
END DESCRIPTION:
XS GIS Cut Line= 3
      1532363.97      6760570.81      1532509.82      6760582.53
      1532697.30      6760583.83
#Sta/Elev= 30
  4849.4 2206.96  4870.5 2205.53  4876.1 2203.33  4881.1 2204.13  4900.6 2203.04
  4910.6 2200.95  4940.7 2190.17  4950.8 2187.69  4960.8 2181.84  4970.8 2184.30
  4980.8 2182.15  4990.8 2175.94  4995.7 2175.94  5000.9 2170.27  5008.9 2167.54
  5009.1 2167.04  5012.9 2167.54  5030.9 2168.31  5040.9 2170.04  5050.9 2176.03
  5059.6 2185.25  5064.6 2187.81  5070.9 2197.30  5090.9 2205.62  5100.9 2207.74
  5120.9 2210.16  5150.9 2209.93  5170.9 2213.05  5179.6 2215.64  5183.2 2215.64
#Mann=3,-1,0
  4849.4    0.07       0  5008.9    0.07       0  5012.9    0.07       0
Bank Sta=5008.9,5012.9
Exp/Cntr=0.3,0.1

Type RM Length L Ch R = 1,3230,57,57,57
BEGIN DESCRIPTION:
Elm 77 3229.84
END DESCRIPTION:
XS GIS Cut Line= 3
      1532328.82      6760608.57      1532502.01      6760641.12
      1532671.98      6760641.12
#Sta/Elev= 30
  4828.3 2216.57  4834.6 2214.41  4851.1 2211.29  4856.2 2211.78  4885.5 2209.09
  4895.6 2206.94  4903.6 2202.78  4908.7 2201.42  4916.0 2195.80  4926.2 2191.53
  4946.5 2185.52  4956.1 2181.46  4966.9 2174.61  4987.2 2165.68  4995.4 2165.66
  4995.6 2165.16  4999.1 2165.16  4999.4 2165.66  5003.5 2171.23  5008.5 2171.23
  5017.5 2176.53  5037.5 2182.52  5047.5 2189.00  5057.5 2194.16  5087.5 2197.43
  5097.5 2200.79  5107.5 2204.93  5117.5 2206.94  5147.5 2208.63  5174.5 2211.99
#Mann=3,-1,0
  4828.3    0.07       0  4995.4    0.07       0  4999.4    0.07       0
Bank Sta=4995.4,4999.4
Exp/Cntr=0.3,0.1

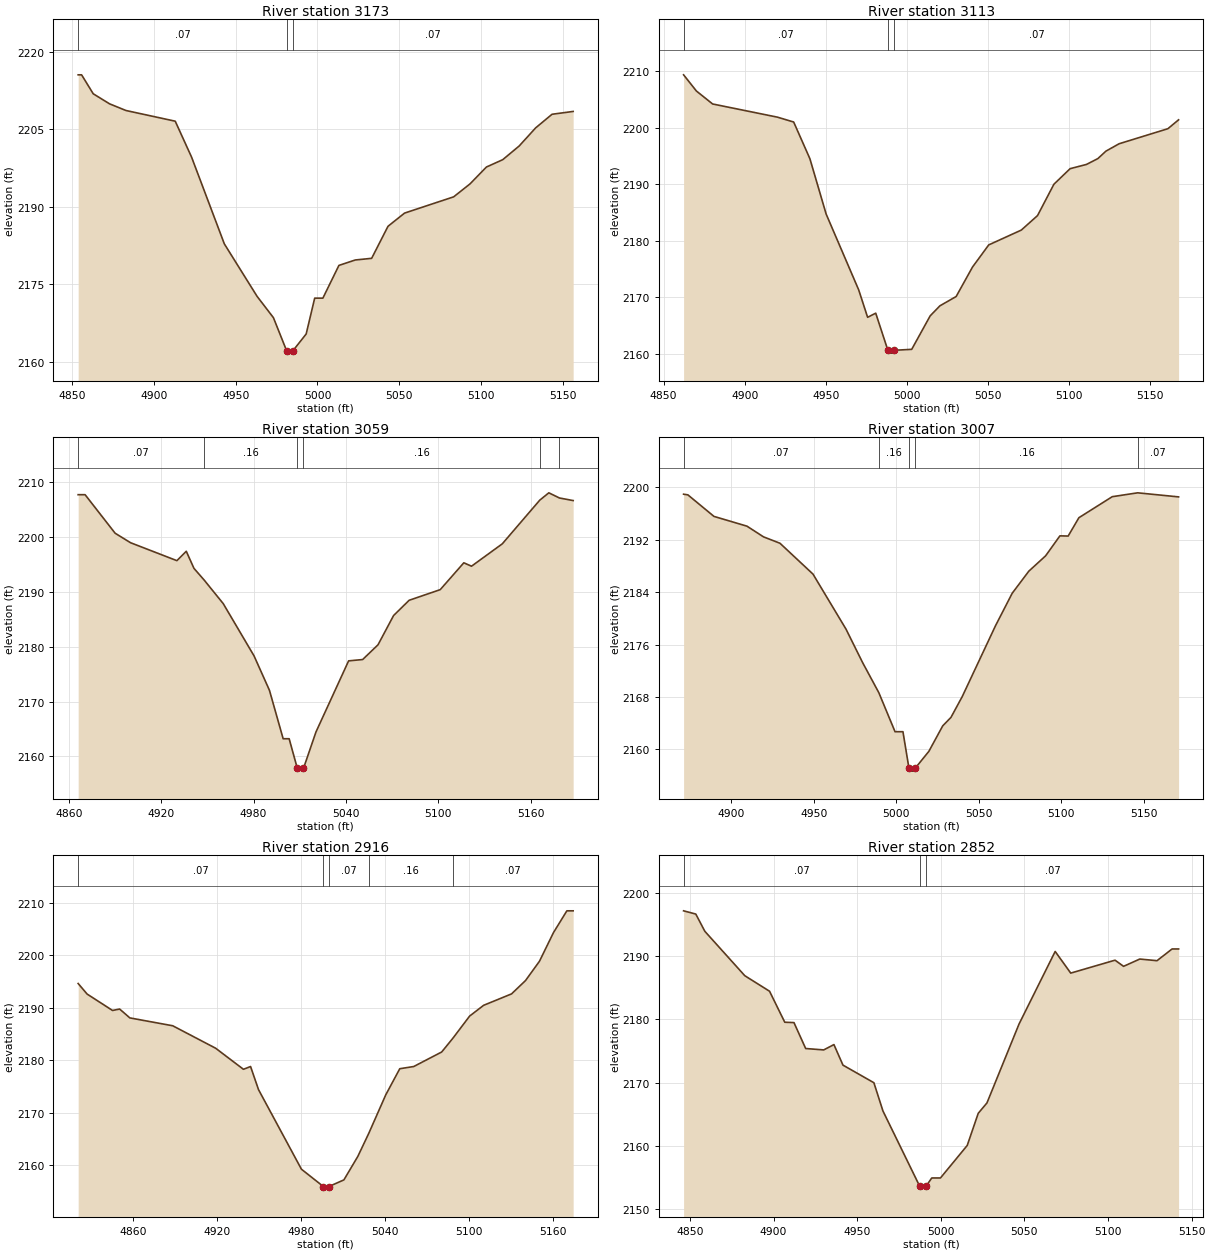
Type RM Length L Ch R = 1,3173,60,60,60
BEGIN DESCRIPTION:
Elm 77 3173.3
END DESCRIPTION:
XS GIS Cut Line= 3
      1532315.76      6760688.00      1532460.34      6760684.09
      1532617.92      6760691.91
#Sta/Elev= 30
  4853.8 2215.54  4855.9 2215.54  4863.0 2211.87  4873.0 2209.92  4883.0 2208.63
  4913.1 2206.56  4923.1 2199.59  4943.1 2182.80  4963.1 2172.64  4973.1 2168.50
  4981.1 2162.14  4981.3 2161.64  4984.8 2161.64  4985.1 2162.14  4993.1 2165.35
  4998.3 2172.29  5003.3 2172.29  5013.1 2178.63  5023.1 2179.68  5033.1 2180.00
  5043.1 2186.21  5053.2 2188.76  5083.2 2191.91  5093.2 2194.42  5103.2 2197.68
  5113.2 2199.11  5123.2 2201.75  5133.3 2205.27  5143.3 2207.90  5156.2 2208.45
#Mann=3,-1,0
  4853.8    0.07       0  4981.1    0.07       0  4985.1    0.07       0
Bank Sta=4981.1,4985.1
Exp/Cntr=0.3,0.1

Type RM Length L Ch R = 1,3113,54,54,54
BEGIN DESCRIPTION:
Elm 77 3112.53
END DESCRIPTION:
XS GIS Cut Line= 3
      1532317.11      6760738.78      1532457.73      6760743.99
      1532621.59      6760728.51
#Sta/Elev= 30
  4862.3 2209.33  4870.2 2206.47  4880.2 2204.18  4920.2 2201.85  4930.2 2200.99
  4940.2 2194.51  4950.2 2184.75  4970.3 2171.33  4975.8 2166.49  4980.8 2167.22
  4988.3 2160.66  4988.5 2160.16  4992.0 2160.16  4992.3 2160.66  5003.0 2160.83
  5014.4 2166.75  5020.4 2168.52  5030.4 2170.16  5040.5 2175.37  5050.5 2179.28
  5070.6 2181.90  5080.6 2184.46  5090.7 2190.00  5100.7 2192.75  5110.8 2193.50
  5117.8 2194.53  5122.8 2195.85  5130.9 2197.15  5161.0 2199.81  5167.6 2201.38
#Mann=3,-1,0
  4862.3    0.07       0  4988.3    0.07       0  4992.3    0.07       0
Bank Sta=4988.3,4992.3
Exp/Cntr=0.3,0.1

Type RM Length L Ch R = 1,3059,52,52,52
BEGIN DESCRIPTION:
Elm 77 3059.24
END DESCRIPTION:
XS GIS Cut Line= 3
      1532321.03      6760788.26      1532457.73      6760797.37
      1532640.65      6760774.02
#Sta/Elev= 30
  4866.1 2207.69  4870.6 2207.69  4890.1 2200.67  4900.1 2198.94  4930.2 2195.67
  4936.3 2197.38  4941.3 2194.26  4947.9 2192.14  4960.3 2187.84  4980.3 2178.32
  4990.3 2172.05  4999.2 2163.22  5003.1 2163.22  5008.4 2157.82  5008.7 2157.32
  5012.4 2157.82  5020.5 2164.45  5041.7 2177.41  5050.8 2177.65  5060.8 2180.34
  5070.9 2185.67  5081.0 2188.45  5101.2 2190.39  5116.5 2195.28  5121.5 2194.66
  5141.5 2198.74  5165.8 2206.69  5171.7 2208.03  5178.6 2207.09  5187.5 2206.62
#Mann=6,-1,0
  4866.1    0.07       0  4947.9    0.16       0  5008.4    0.07       0
  5012.4    0.16       0  5165.8    0.07       0  5178.6    0.16       0
Bank Sta=5008.4,5012.4
Exp/Cntr=0.3,0.1

Type RM Length L Ch R = 1,3007,91,91,91
BEGIN DESCRIPTION:
Elm 77 3007.43
END DESCRIPTION:
XS GIS Cut Line= 3
      1532336.65      6760842.95      1532469.45      6760846.85
      1532634.84      6760823.41
#Sta/Elev= 30
  4871.2 2198.96  4873.8 2198.86  4889.6 2195.57  4909.6 2194.08  4919.6 2192.45
  4929.6 2191.47  4949.6 2186.76  4969.6 2178.36  4979.6 2173.28  4989.5 2168.65
  4999.3 2162.70  5004.1 2162.70  5007.7 2157.18  5007.9 2156.68  5011.4 2156.68
  5011.7 2157.18  5019.8 2159.70  5028.2 2163.59  5033.2 2164.89  5040.0 2168.05
  5060.2 2178.89  5070.3 2183.84  5080.4 2187.22  5090.5 2189.54  5099.2 2192.60
  5104.2 2192.57  5110.7 2195.37  5130.9 2198.58  5146.3 2199.17  5171.1 2198.55
#Mann=5,-1,0
  4871.2    0.07       0  4989.5    0.16       0  5007.7    0.07       0
  5011.7    0.16       0  5146.3    0.07       0
Bank Sta=5007.7,5011.7
Exp/Cntr=0.3,0.1

Type RM Length L Ch R = 1,2916,64,64,64
BEGIN DESCRIPTION:
Elm 77 2915.6
END DESCRIPTION:
XS GIS Cut Line= 3
      1532328.79      6760887.21      1532504.61      6760924.98
      1532679.07      6760926.28
#Sta/Elev= 30
  4820.4 2194.64  4826.8 2192.63  4845.0 2189.50  4850.1 2189.77  4857.4 2188.08
  4888.1 2186.58  4918.8 2182.30  4938.7 2178.28  4943.8 2178.81  4949.5 2174.40
  4980.2 2159.23  4995.9 2155.93  4996.1 2155.43  4999.9 2155.93  5010.6 2157.19
  5020.6 2161.68  5028.5 2166.12  5040.6 2173.43  5050.6 2178.39  5060.6 2178.81
  5080.6 2181.58  5088.6 2184.20  5100.6 2188.43  5110.6 2190.48  5130.6 2192.66
  5140.6 2195.20  5150.6 2198.89  5160.6 2204.34  5170.2 2208.50  5174.7 2208.50
#Mann=5,-1,0
  4820.4    0.07       0  4995.9    0.07       0  4999.9    0.07       0
  5028.5    0.16       0  5088.6    0.07       0
Bank Sta=4995.9,4999.9
Exp/Cntr=0.3,0.1

Type RM Length L Ch R = 1,2852,68,68,68
BEGIN DESCRIPTION:
Elm 77 2852.03
END DESCRIPTION:
XS GIS Cut Line= 3
      1532327.51      6760918.46      1532469.45      6760977.06
      1532607.48      6761012.22
#Sta/Elev= 30
  4846.2 2197.13  4853.5 2196.62  4858.9 2193.90  4882.8 2186.89  4897.6 2184.44
  4906.7 2179.55  4912.2 2179.49  4919.2 2175.40  4930.0 2175.18  4936.1 2176.02
  4941.5 2172.78  4960.0 2170.00  4965.4 2165.55  4987.3 2153.71  4987.6 2153.21
  4991.3 2153.71  4994.6 2154.97  4999.8 2154.97  5015.8 2160.10  5022.4 2165.18
  5027.6 2166.81  5046.8 2179.27  5068.4 2190.72  5077.7 2187.30  5104.2 2189.34
  5109.3 2188.37  5119.0 2189.52  5129.3 2189.26  5138.3 2191.11  5142.2 2191.11
#Mann=3,-1,0
  4846.2    0.07       0  4987.3    0.07       0  4991.3    0.07       0
Bank Sta=4987.3,4991.3
Exp/Cntr=0.3,0.1

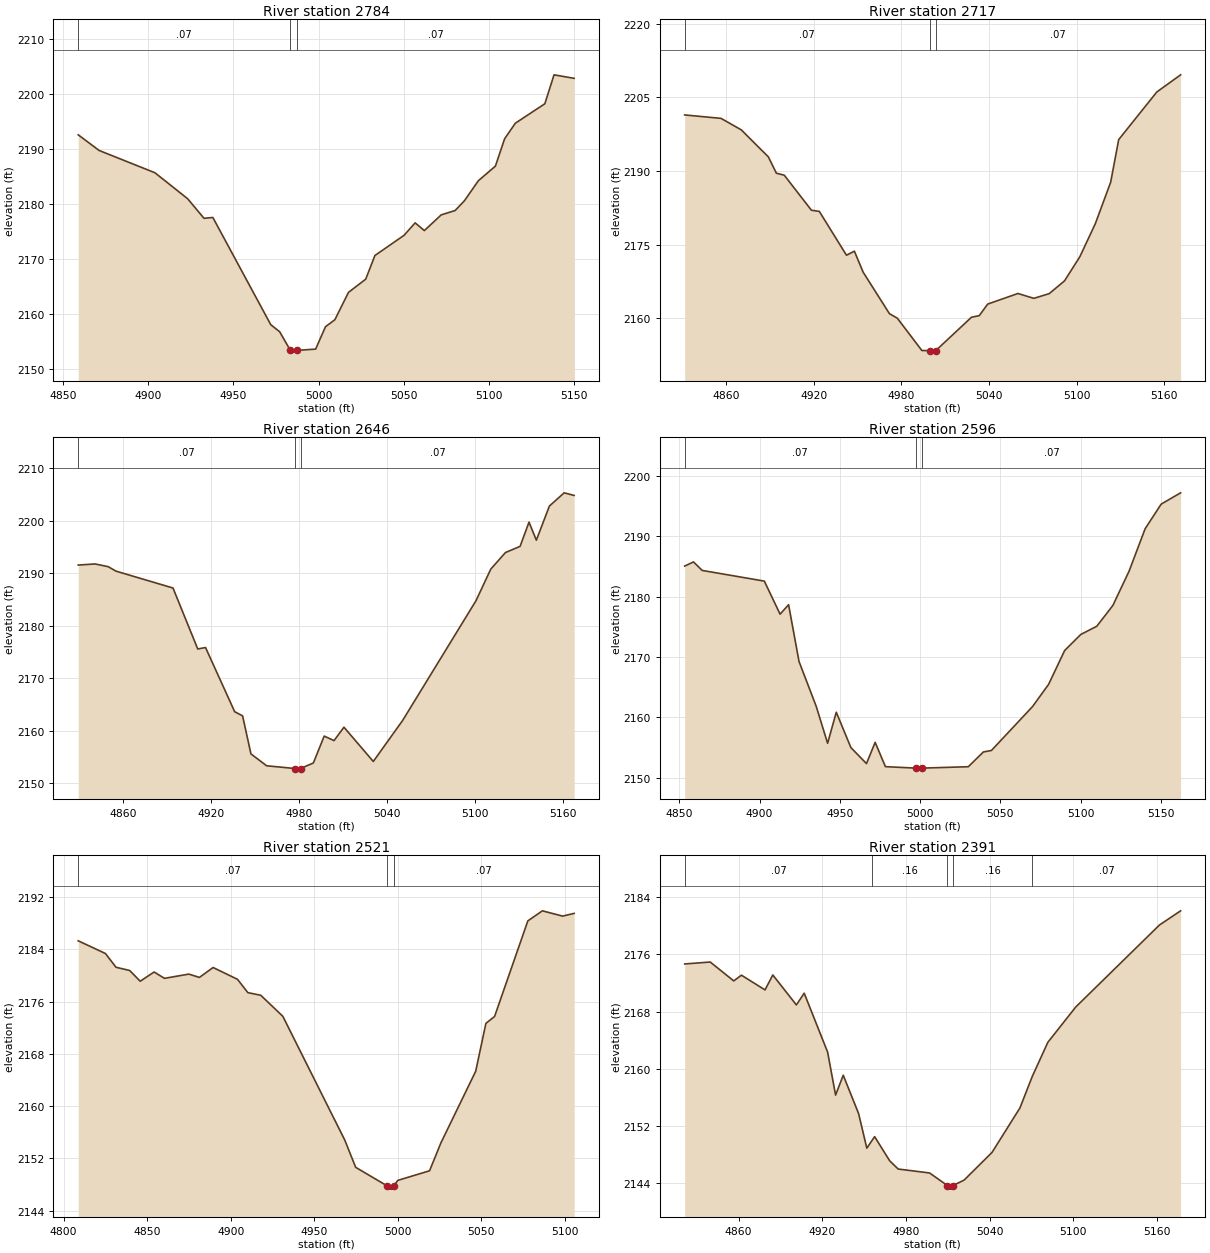
Type RM Length L Ch R = 1,2784,67,67,67
BEGIN DESCRIPTION:
Elm 77 2784.1
END DESCRIPTION:
XS GIS Cut Line= 3
      1532313.20      6761001.80      1532447.32      6761039.56
      1532586.65      6761099.46
#Sta/Elev= 30
  4859.0 2192.62  4871.3 2189.77  4904.0 2185.73  4923.2 2181.01  4932.8 2177.45
  4938.0 2177.60  4972.0 2158.11  4977.2 2156.84  4983.5 2153.45  4983.8 2152.95
  4987.5 2153.45  4998.3 2153.68  5004.1 2157.75  5009.6 2159.02  5017.6 2163.99
  5027.7 2166.39  5033.1 2170.69  5050.2 2174.36  5056.7 2176.62  5062.1 2175.22
  5072.0 2178.07  5080.2 2178.87  5085.7 2180.67  5093.8 2184.28  5103.8 2186.93
  5109.2 2191.90  5115.5 2194.73  5132.8 2198.26  5138.2 2203.52  5150.0 2202.88
#Mann=3,-1,0
  4859.0    0.07       0  4983.5    0.07       0  4987.5    0.07       0
Bank Sta=4983.5,4987.5
Exp/Cntr=0.3,0.1

Type RM Length L Ch R = 1,2717,71,71,71
BEGIN DESCRIPTION:
Elm 77 2717.15
END DESCRIPTION:
XS GIS Cut Line= 3
      1532251.97      6761029.13      1532404.35      6761091.64
      1532570.53      6761146.17
#Sta/Elev= 30
  4831.6 2201.43  4856.5 2200.73  4870.4 2198.38  4888.9 2192.88  4894.4 2189.55
  4899.8 2189.14  4918.4 2182.00  4923.8 2181.76  4942.4 2172.82  4947.8 2173.65
  4953.8 2169.37  4971.8 2160.91  4977.2 2159.99  4994.0 2153.40  4999.5 2153.36
  4999.7 2152.86  5003.5 2153.36  5028.0 2160.18  5033.3 2160.50  5039.1 2162.86
  5059.8 2165.02  5070.7 2164.03  5081.2 2164.99  5091.7 2167.59  5102.2 2172.52
  5112.8 2179.26  5123.3 2187.71  5128.8 2196.40  5154.9 2206.11  5171.2 2209.61
#Mann=3,-1,0
  4831.6    0.07       0  4999.5    0.07       0  5003.5    0.07       0
Bank Sta=4999.5,5003.5
Exp/Cntr=0.3,0.1

Type RM Length L Ch R = 1,2646,50,50,50
BEGIN DESCRIPTION:
Elm 77 2646.37
END DESCRIPTION:
XS GIS Cut Line= 3
      1532244.24      6761104.68      1532408.26      6761164.56
      1532571.83      6761174.87
#Sta/Elev= 30
  4829.1 2191.52  4840.6 2191.73  4849.6 2191.21  4854.9 2190.36  4893.8 2187.15
  4910.7 2175.54  4916.0 2175.82  4935.9 2163.60  4941.3 2162.81  4947.0 2155.57
  4957.7 2153.31  4976.9 2152.79  4977.2 2152.29  4980.7 2152.29  4980.9 2152.79
  4989.6 2153.84  4997.0 2158.96  5003.7 2158.10  5010.5 2160.65  5030.5 2154.13
  5050.5 2161.92  5100.6 2184.73  5110.7 2190.75  5120.7 2193.90  5130.7 2195.08
  5136.8 2199.69  5141.8 2196.25  5150.7 2202.75  5160.8 2205.27  5167.6 2204.77
#Mann=3,-1,0
  4829.1    0.07       0  4976.9    0.07       0  4980.9    0.07       0
Bank Sta=4976.9,4980.9
Exp/Cntr=0.3,0.1

Type RM Length L Ch R = 1,2596,75,75,75
BEGIN DESCRIPTION:
Elm 77 2595.87
END DESCRIPTION:
XS GIS Cut Line= 3
      1532268.92      6761159.35      1532405.65      6761214.04
      1532567.14      6761210.13
#Sta/Elev= 30
  4853.4 2185.06  4858.9 2185.75  4864.3 2184.34  4903.0 2182.57  4912.8 2177.09
  4918.1 2178.66  4924.6 2169.25  4935.3 2161.82  4942.4 2155.70  4947.8 2160.84
  4956.9 2154.98  4966.6 2152.33  4972.0 2155.85  4978.4 2151.82  4997.3 2151.58
  4997.5 2151.08  5001.3 2151.58  5030.0 2151.81  5039.4 2154.26  5044.4 2154.50
  5070.0 2161.78  5080.0 2165.46  5090.0 2171.07  5100.0 2173.72  5110.0 2175.09
  5120.0 2178.53  5130.1 2184.21  5140.1 2191.24  5150.1 2195.33  5162.2 2197.20
#Mann=3,-1,0
  4853.4    0.07       0  4997.3    0.07       0  5001.3    0.07       0
Bank Sta=4997.3,5001.3
Exp/Cntr=0.3,0.1

Type RM Length L Ch R = 1,2521,130,130,130
BEGIN DESCRIPTION:
Elm 77 2520.84
END DESCRIPTION:
XS GIS Cut Line= 3
      1532248.08      6761172.36      1532400.44      6761288.26
      1532501.63      6761317.28
#Sta/Elev= 30
  4808.8 2185.31  4825.1 2183.36  4831.4 2181.26  4839.6 2180.76  4845.9 2179.12
  4854.2 2180.53  4860.4 2179.56  4875.0 2180.21  4881.3 2179.70  4889.5 2181.22
  4904.1 2179.41  4910.3 2177.37  4918.0 2176.97  4931.2 2173.75  4968.3 2154.78
  4974.8 2150.62  4993.6 2147.78  4993.9 2147.28  4997.4 2147.28  4997.6 2147.78
  5000.0 2148.62  5019.0 2150.09  5025.8 2154.37  5046.6 2165.33  5052.7 2172.66
  5057.9 2173.72  5077.8 2188.36  5086.5 2189.90  5098.6 2189.09  5105.5 2189.51
#Mann=3,-1,0
  4808.8    0.07       0  4993.6    0.07       0  4997.6    0.07       0
Bank Sta=4993.6,4997.6
Exp/Cntr=0.3,0.1

Type RM Length L Ch R = 1,2391,64,64,64
BEGIN DESCRIPTION:
Elm 77 2390.98
END DESCRIPTION:
XS GIS Cut Line= 3
      1532153.07      6761305.20      1532314.51      6761384.61
      1532490.19      6761384.61
#Sta/Elev= 30
  4821.3 2174.65  4839.6 2174.92  4856.5 2172.28  4862.0 2173.08  4878.9 2171.02
  4884.5 2173.11  4901.4 2168.92  4907.0 2170.56  4923.8 2162.32  4929.5 2156.31
  4935.0 2159.09  4946.0 2153.73  4951.9 2148.89  4955.8 2150.01  4957.5 2150.50
  4968.3 2147.12  4974.4 2145.97  4996.9 2145.42  5009.7 2143.66  5010.0 2143.16
  5013.5 2143.16  5013.7 2143.66  5021.7 2144.43  5041.7 2148.30  5061.7 2154.52
  5070.6 2158.95  5081.7 2163.69  5101.7 2168.63  5161.7 2180.09  5176.9 2182.08
#Mann=5,-1,0
  4821.3    0.07       0  4955.8    0.16       0  5009.7    0.07       0
  5013.7    0.16       0  5070.6    0.07       0
Bank Sta=5009.7,5013.7
Exp/Cntr=0.3,0.1

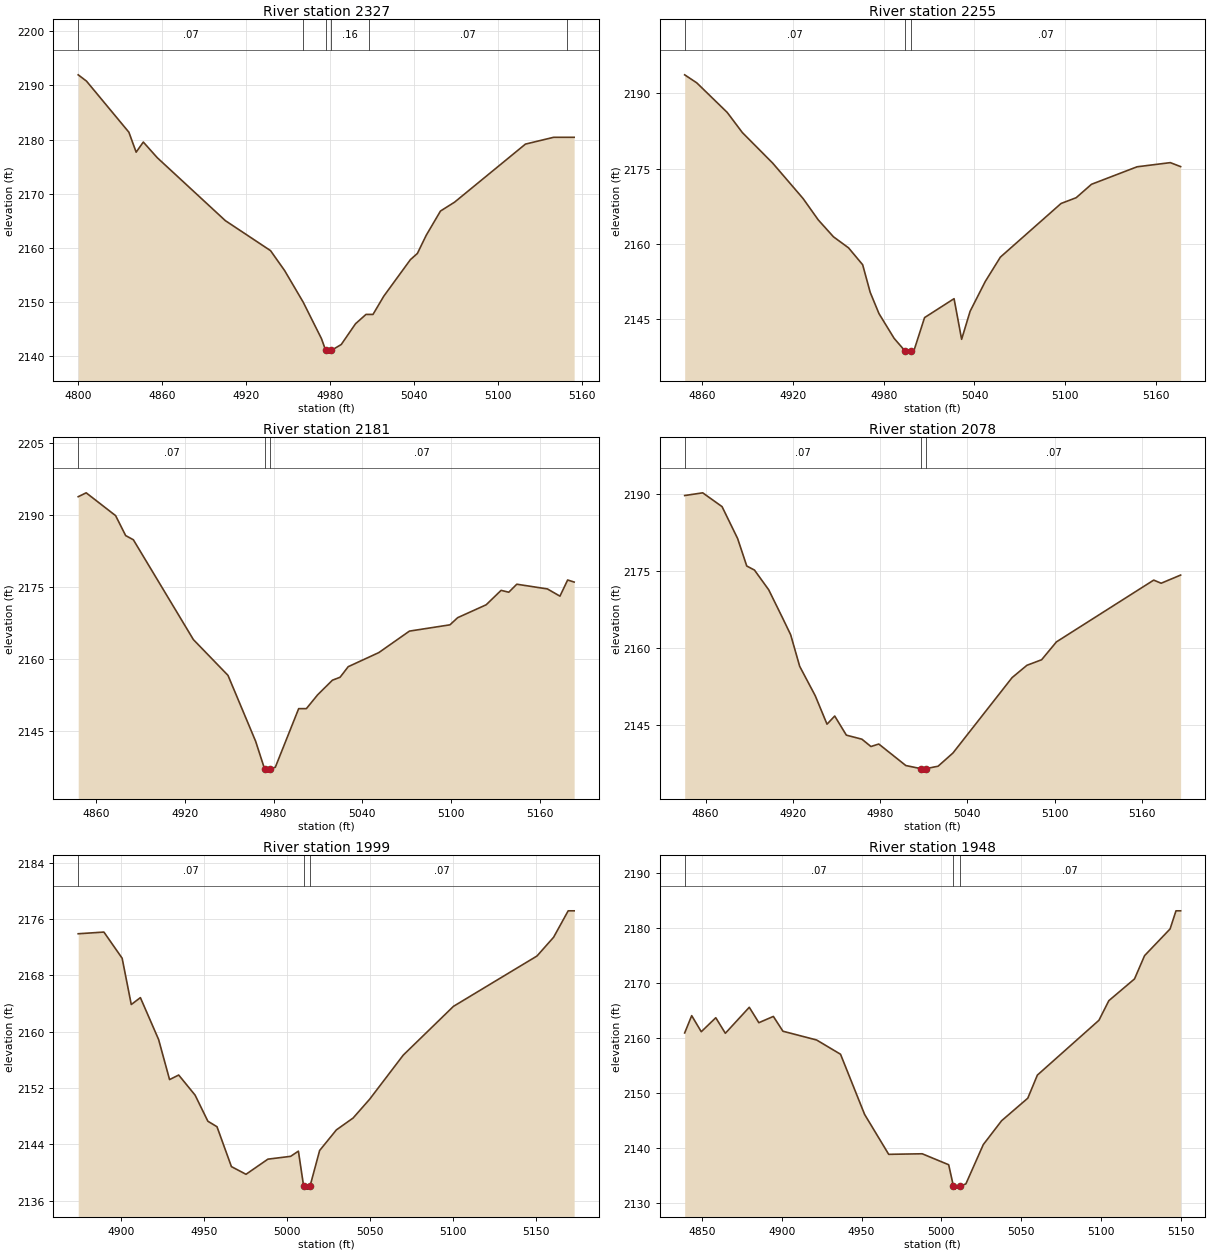
Type RM Length L Ch R = 1,2327,72,72,72
BEGIN DESCRIPTION:
Elm 77 2327.1
END DESCRIPTION:
XS GIS Cut Line= 3
      1532149.19      6761406.76      1532354.87      6761438.00
      1532499.44      6761415.86
#Sta/Elev= 30
  4800.3 2191.96  4806.2 2190.80  4836.5 2181.35  4841.7 2177.66  4846.8 2179.53
  4856.8 2176.63  4905.4 2165.00  4937.7 2159.45  4947.8 2155.75  4961.0 2149.94
  4974.1 2143.17  4977.1 2141.00  4977.4 2140.50  4980.9 2140.50  4981.1 2141.00
  4988.2 2142.09  4998.4 2145.93  5005.9 2147.66  5008.3 2147.66  5010.9 2147.66
  5018.6 2151.03  5037.6 2157.78  5042.6 2158.93  5048.9 2162.28  5059.1 2166.77
  5069.2 2168.42  5119.8 2179.15  5140.0 2180.41  5149.6 2180.41  5154.6 2180.41
#Mann=6,-1,0
  4800.3    0.07       0  4961.0    0.16       0  4977.1    0.07       0
  4981.1    0.16       0  5008.3    0.07       0  5149.6    0.16       0
Bank Sta=4977.1,4981.1
Exp/Cntr=0.3,0.1

Type RM Length L Ch R = 1,2255,74,74,74
BEGIN DESCRIPTION:
Elm 77 2255.39
END DESCRIPTION:
XS GIS Cut Line= 3
      1532157.00      6761483.58      1532307.99      6761495.29
      1532483.76      6761482.27
#Sta/Elev= 30
  4848.5 2193.70  4856.5 2192.10  4876.6 2186.22  4886.6 2182.21  4906.7 2176.11
  4926.7 2169.09  4936.8 2164.81  4946.8 2161.46  4956.8 2159.25  4966.1 2155.90
  4971.1 2150.39  4976.9 2146.16  4986.9 2141.24  4993.9 2138.80  4994.2 2138.30
  4997.7 2138.30  4997.9 2138.80  5000.0 2138.80  5007.0 2145.37  5026.5 2149.14
  5031.5 2141.05  5037.1 2146.63  5047.1 2152.55  5057.1 2157.41  5097.2 2168.09
  5107.2 2169.24  5117.3 2171.91  5147.4 2175.39  5169.4 2176.22  5176.2 2175.43
#Mann=3,-1,0
  4848.5    0.07       0  4993.9    0.07       0  4997.9    0.07       0
Bank Sta=4993.9,4997.9
Exp/Cntr=0.3,0.1

Type RM Length L Ch R = 1,2181,103,103,103
BEGIN DESCRIPTION:
Elm 77 2180.86
END DESCRIPTION:
XS GIS Cut Line= 3
      1532160.89      6761522.65      1532305.39      6761569.51
      1532482.45      6761521.34
#Sta/Elev= 30
  4847.9 2193.85  4853.3 2194.66  4873.2 2189.90  4880.0 2185.74  4885.2 2184.87
  4925.8 2164.05  4949.2 2156.59  4967.9 2142.84  4973.9 2137.12  4974.2 2136.62
  4977.9 2137.12  4981.2 2137.43  4997.0 2149.65  5002.2 2149.65  5009.8 2152.53
  5019.8 2155.58  5025.0 2156.20  5030.5 2158.40  5051.2 2161.34  5071.9 2165.82
  5099.3 2167.13  5104.5 2168.62  5123.8 2171.31  5133.9 2174.32  5139.1 2173.93
  5144.5 2175.60  5165.2 2174.62  5173.7 2173.11  5178.9 2176.48  5183.3 2176.05
#Mann=3,-1,0
  4847.9    0.07       0  4973.9    0.07       0  4977.9    0.07       0
Bank Sta=4973.9,4977.9
Exp/Cntr=0.3,0.1

Type RM Length L Ch R = 1,2078,79,79,79
BEGIN DESCRIPTION:
Elm 77 2078.41
END DESCRIPTION:
XS GIS Cut Line= 3
      1532160.89      6761617.70      1532306.69      6761672.37
      1532488.96      6761706.22
#Sta/Elev= 30
  4845.6 2189.72  4858.0 2190.25  4871.3 2187.56  4882.0 2181.34  4888.3 2175.97
  4893.6 2175.18  4903.4 2171.33  4913.2 2165.68  4918.5 2162.56  4924.7 2156.40
  4935.4 2150.66  4943.5 2145.11  4948.8 2146.70  4956.8 2142.97  4967.5 2142.18
  4973.7 2140.75  4979.1 2141.24  4997.7 2137.04  5007.8 2136.45  5008.0 2135.95
  5011.8 2136.45  5019.9 2136.91  5030.1 2139.48  5070.8 2154.20  5081.0 2156.60
  5091.1 2157.68  5101.3 2161.17  5168.2 2173.22  5173.3 2172.61  5186.7 2174.20
#Mann=3,-1,0
  4845.6    0.07       0  5007.8    0.07       0  5011.8    0.07       0
Bank Sta=5007.8,5011.8
Exp/Cntr=0.3,0.1

Type RM Length L Ch R = 1,1999,51,51,51
BEGIN DESCRIPTION:
Elm 77 1998.53
END DESCRIPTION:
XS GIS Cut Line= 3
      1532190.85      6761699.74      1532305.39      6761751.80
      1532477.25      6761773.93
#Sta/Elev= 30
  4874.2 2173.93  4889.7 2174.17  4900.7 2170.45  4906.2 2163.87  4911.7 2164.85
  4922.7 2158.89  4929.3 2153.20  4934.8 2153.85  4944.7 2150.99  4952.4 2147.28
  4957.9 2146.50  4966.6 2140.83  4975.4 2139.74  4988.6 2141.89  5002.3 2142.29
  5007.0 2143.03  5010.1 2138.13  5010.3 2137.63  5013.8 2137.63  5014.1 2138.13
  5019.8 2143.12  5029.9 2146.05  5040.0 2147.74  5050.0 2150.42  5070.2 2156.67
  5100.5 2163.61  5150.9 2170.77  5160.9 2173.43  5169.7 2177.19  5173.3 2177.19
#Mann=3,-1,0
  4874.2    0.07       0  5010.1    0.07       0  5014.1    0.07       0
Bank Sta=5010.1,5014.1
Exp/Cntr=0.3,0.1

Type RM Length L Ch R = 1,1948,50,50,50
BEGIN DESCRIPTION:
Elm 77 1947.71
END DESCRIPTION:
XS GIS Cut Line= 3
      1532156.96      6761710.14      1532291.07      6761798.68
      1532425.15      6761866.37
#Sta/Elev= 30
  4839.1 2160.90  4843.5 2164.04  4849.5 2161.12  4858.6 2163.66  4864.6 2160.84
  4879.6 2165.56  4885.6 2162.76  4894.7 2163.90  4900.7 2161.21  4921.8 2159.62
  4936.8 2157.03  4951.9 2146.10  4967.0 2138.85  4988.0 2138.95  5004.6 2136.96
  5007.6 2133.03  5007.9 2132.53  5011.6 2133.03  5015.4 2133.49  5026.3 2140.62
  5037.8 2144.96  5054.2 2149.05  5060.2 2153.24  5098.8 2163.20  5105.0 2166.76
  5121.1 2170.71  5127.4 2174.94  5143.4 2179.79  5147.1 2183.08  5150.0 2183.08
#Mann=3,-1,0
  4839.1    0.07       0  5007.6    0.07       0  5011.6    0.07       0
Bank Sta=5007.6,5011.6
Exp/Cntr=0.3,0.1