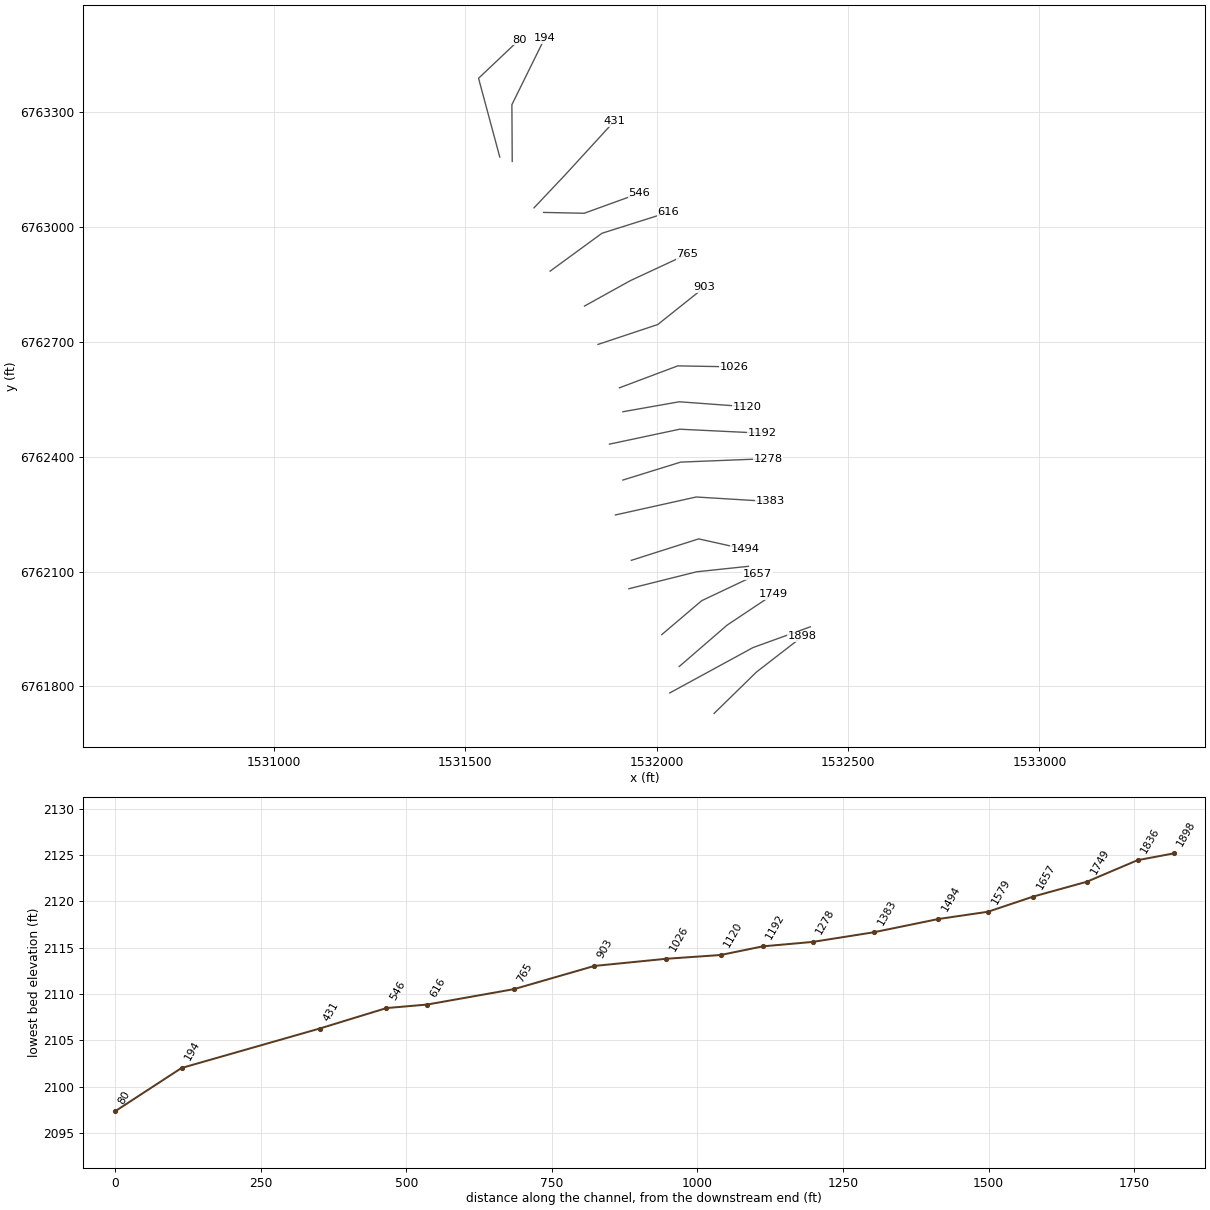
HEC-RAS study Elm 77.prj: Elm 77 Base Level Engineering

--- Elm 77.g01 (geometry) --- (continued)

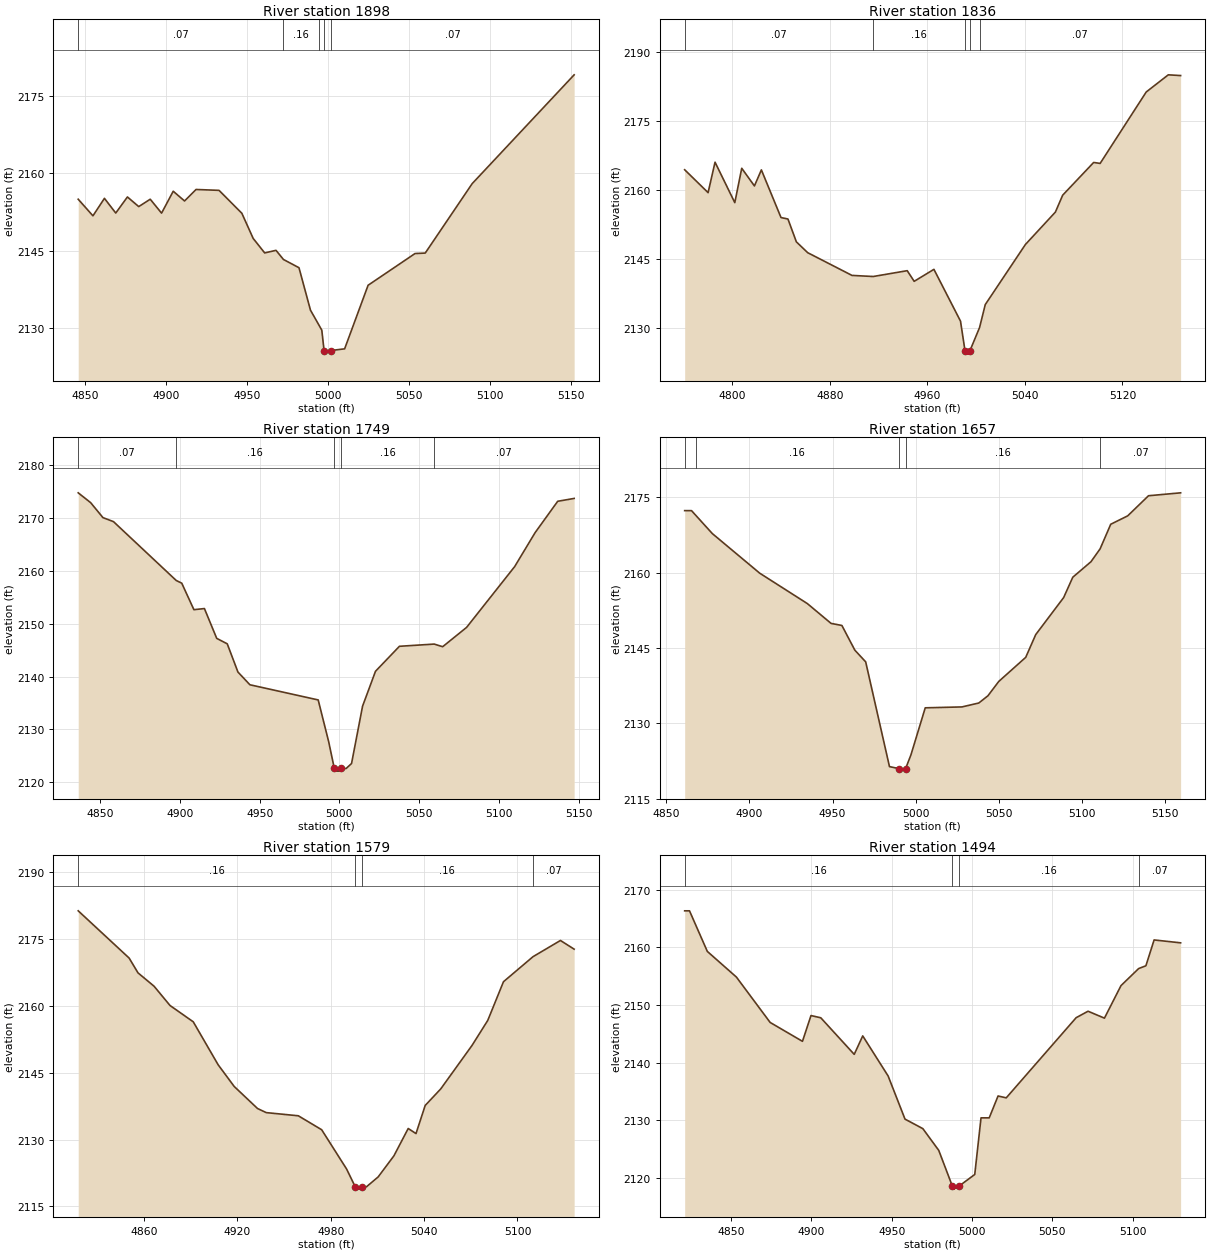
Type RM Length L Ch R = 1,1898,62,62,62
BEGIN DESCRIPTION:
Elm 77 1898.3
END DESCRIPTION:
XS GIS Cut Line= 3
      1532150.44      6761729.66      1532261.12      6761837.74
      1532381.08      6761930.61
#Sta/Elev= 30
  4845.7 2155.00  4854.8 2151.78  4861.9 2155.17  4868.9 2152.32  4876.1 2155.44
  4883.1 2153.57  4890.2 2155.00  4897.2 2152.30  4904.4 2156.55  4911.4 2154.66
  4918.5 2156.89  4932.7 2156.72  4946.8 2152.28  4953.8 2147.40  4960.9 2144.59
  4967.9 2145.09  4972.5 2143.32  4982.1 2141.72  4989.2 2133.49  4994.6 2130.50
  4996.2 2129.61  4997.6 2125.66  4997.9 2125.16  5001.6 2125.66  5010.3 2125.99
  5024.8 2138.32  5053.8 2144.47  5060.1 2144.56  5089.1 2158.02  5152.1 2179.12
#Mann=5,-1,0
  4845.7    0.07       0  4972.5    0.16       0  4994.6    0.07       0
  4997.6    0.07       0  5001.6    0.07       0
Bank Sta=4997.6,5001.6
Exp/Cntr=0.3,0.1

Type RM Length L Ch R = 1,1836,87,87,87
BEGIN DESCRIPTION:
Elm 77 1835.59
END DESCRIPTION:
XS GIS Cut Line= 3
      1532034.52      6761783.03      1532252.01      6761901.54
      1532401.53      6761955.68
#Sta/Elev= 30
  4761.0 2164.40  4780.2 2159.41  4785.9 2166.05  4802.1 2157.23  4807.8 2164.72
  4818.2 2160.87  4823.9 2164.37  4840.0 2153.98  4845.7 2153.66  4852.6 2148.68
  4861.9 2146.32  4898.2 2141.37  4915.6 2141.13  4943.5 2142.40  4949.2 2140.08
  4965.4 2142.69  4987.2 2131.40  4990.9 2124.93  4991.2 2124.43  4994.9 2124.93
  5002.8 2129.99  5007.5 2135.01  5040.4 2148.10  5065.0 2155.17  5071.0 2158.86
  5096.4 2165.99  5101.7 2165.78  5139.5 2181.35  5157.6 2185.09  5167.7 2184.93
#Mann=5,-1,0
  4761.0    0.07       0  4915.6    0.16       0  4990.9    0.07       0
  4994.9    0.16       0  5002.8    0.07       0
Bank Sta=4990.9,4994.9
Exp/Cntr=0.3,0.1

Type RM Length L Ch R = 1,1749,92,92,92
BEGIN DESCRIPTION:
Elm 77 1748.6
END DESCRIPTION:
XS GIS Cut Line= 3
      1532059.26      6761852.03      1532184.30      6761960.13
      1532305.37      6762040.85
#Sta/Elev= 30
  4836.3 2174.77  4844.1 2172.91  4851.8 2170.08  4858.4 2169.32  4897.7 2158.19
  4901.2 2157.67  4908.8 2152.66  4915.4 2152.87  4923.1 2147.23  4929.7 2146.20
  4936.4 2140.86  4943.9 2138.45  4986.7 2135.58  4993.3 2127.63  4996.8 2122.61
  4997.0 2122.11  5000.5 2122.11  5000.8 2122.61  5004.2 2122.61  5007.6 2123.55
  5014.5 2134.40  5022.6 2141.00  5037.6 2145.73  5059.4 2146.15  5064.7 2145.65
  5079.7 2149.31  5109.8 2160.80  5122.6 2167.22  5136.8 2173.17  5147.1 2173.71
#Mann=5,-1,0
  4836.3    0.07       0  4897.7    0.16       0  4996.8    0.07       0
  5000.8    0.16       0  5059.4    0.07       0
Bank Sta=4996.8,5000.8
Exp/Cntr=0.3,0.1

Type RM Length L Ch R = 1,1657,78,78,78
BEGIN DESCRIPTION:
Elm 77 1657.22
END DESCRIPTION:
XS GIS Cut Line= 3
      1532013.72      6761935.39      1532117.89      6762023.94
      1532263.76      6762092.97
#Sta/Elev= 30
  4861.1 2172.32  4865.2 2172.32  4867.7 2171.41  4877.7 2167.76  4906.2 2159.88
  4934.8 2153.84  4949.1 2149.89  4955.6 2149.48  4963.4 2144.56  4969.9 2142.24
  4984.2 2121.41  4989.9 2121.01  4990.2 2120.51  4993.9 2121.01  4997.1 2123.74
  5005.7 2133.10  5027.8 2133.28  5037.9 2134.06  5043.4 2135.50  5049.9 2138.35
  5066.1 2143.14  5072.1 2147.66  5088.9 2155.03  5094.4 2159.08  5105.3 2162.15
  5110.8 2164.71  5117.2 2169.61  5127.4 2171.28  5139.9 2175.28  5159.2 2175.86
#Mann=5,-1,0
  4861.1    0.07       0  4867.7    0.16       0  4989.9    0.07       0
  4993.9    0.16       0  5110.8    0.07       0
Bank Sta=4989.9,4993.9
Exp/Cntr=0.3,0.1

Type RM Length L Ch R = 1,1579,85,85,85
BEGIN DESCRIPTION:
Elm 77 1578.69
END DESCRIPTION:
XS GIS Cut Line= 3
      1531927.79      6762055.19      1532104.87      6762099.46
      1532240.19      6762113.77
#Sta/Elev= 30
  4817.8 2181.29  4850.5 2170.70  4856.2 2167.38  4866.5 2164.39  4876.8 2160.05
  4891.7 2156.40  4907.7 2146.76  4918.0 2141.90  4933.0 2136.95  4938.6 2136.03
  4959.2 2135.32  4974.2 2132.19  4990.2 2123.39  4995.8 2119.37  4996.1 2118.87
  4999.6 2118.87  4999.8 2119.37  5002.9 2119.37  5010.5 2121.61  5020.6 2126.33
  5029.8 2132.47  5034.8 2131.33  5040.7 2137.63  5050.7 2141.35  5070.8 2151.10
  5080.9 2156.71  5091.0 2165.39  5110.0 2171.01  5127.6 2174.64  5136.4 2172.69
#Mann=4,-1,0
  4817.8    0.16       0  4995.8    0.07       0  4999.8    0.16       0
  5110.0    0.07       0
Bank Sta=4995.8,4999.8
Exp/Cntr=0.3,0.1

Type RM Length L Ch R = 1,1494,111,111,111
BEGIN DESCRIPTION:
Elm 77 1494.38
END DESCRIPTION:
XS GIS Cut Line= 3
      1531934.33      6762129.42      1532110.08      6762185.39
      1532231.24      6762158.33
#Sta/Elev= 30
  4821.2 2166.35  4824.2 2166.35  4835.3 2159.31  4853.4 2154.86  4874.4 2146.99
  4894.5 2143.72  4899.8 2148.19  4905.9 2147.80  4926.7 2141.46  4932.0 2144.66
  4947.8 2137.71  4958.3 2130.23  4969.4 2128.58  4979.3 2124.81  4987.8 2118.59
  4988.1 2118.09  4991.8 2118.59  5001.7 2120.63  5005.6 2130.45  5010.7 2130.45
  5016.2 2134.24  5021.3 2133.92  5064.8 2147.82  5072.2 2148.94  5082.4 2147.74
  5092.7 2153.38  5103.7 2156.34  5108.2 2156.82  5113.3 2161.30  5129.8 2160.80
#Mann=4,-1,0
  4821.2    0.16       0  4987.8    0.07       0  4991.8    0.16       0
  5103.7    0.07       0
Bank Sta=4987.8,4991.8
Exp/Cntr=0.3,0.1

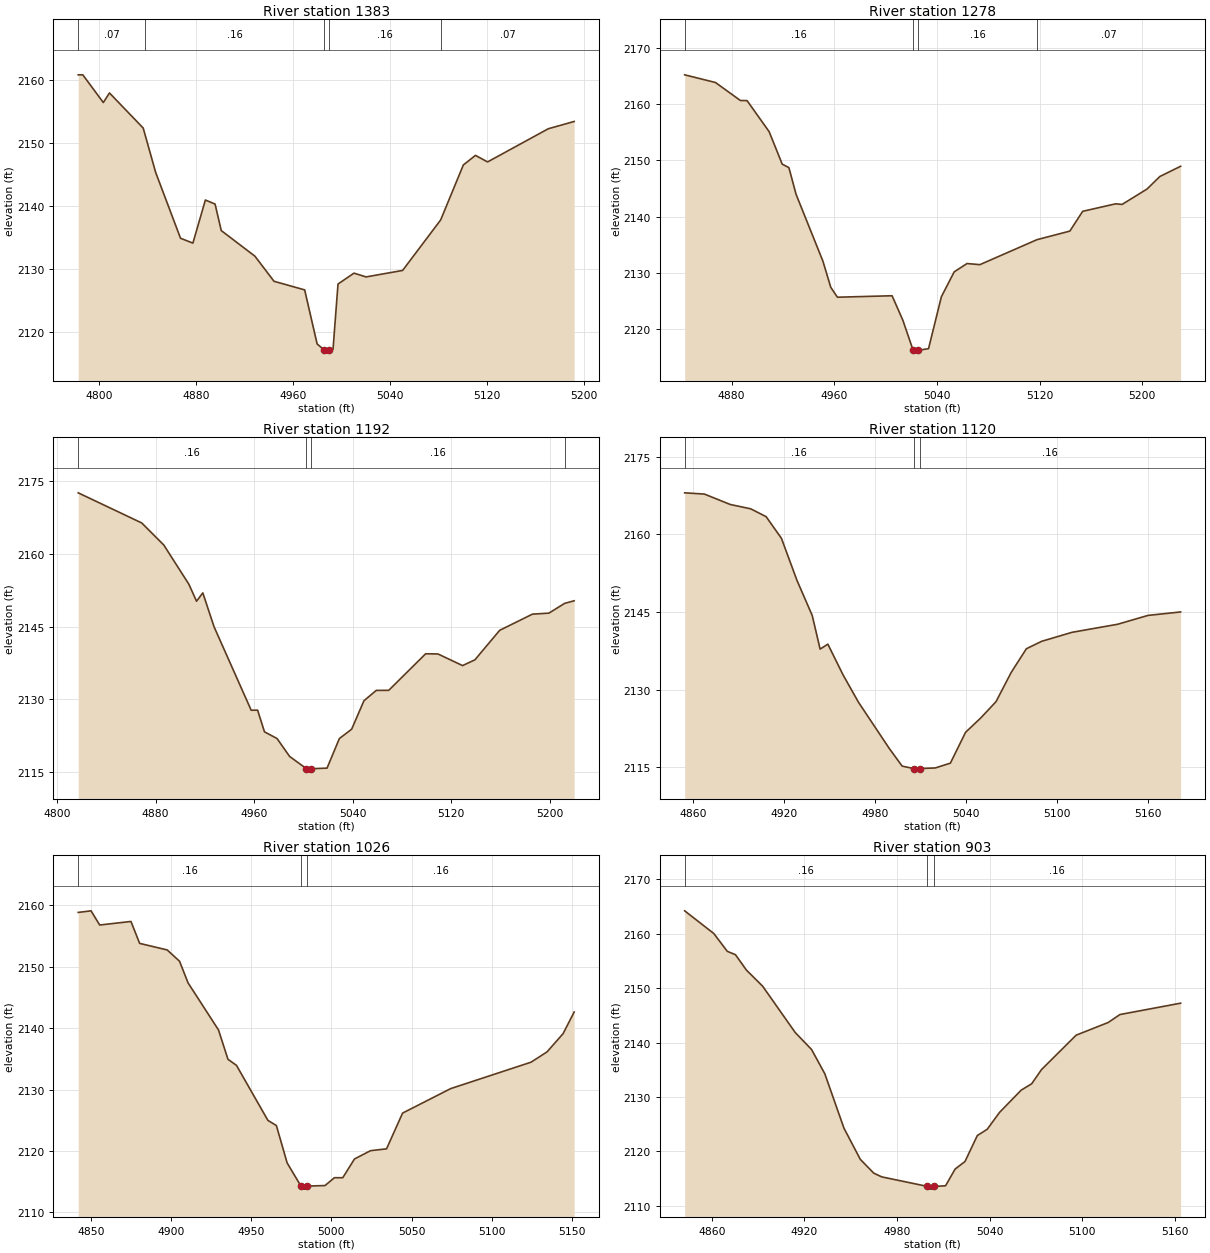
Type RM Length L Ch R = 1,1383,105,105,105
BEGIN DESCRIPTION:
Elm 77 1383.38
END DESCRIPTION:
XS GIS Cut Line= 3
      1531892.64      6762247.90      1532103.57      6762294.77
      1532296.23      6762283.05
#Sta/Elev= 30
  4782.6 2160.85  4786.4 2160.85  4803.3 2156.45  4808.4 2157.97  4836.2 2152.40
  4837.9 2151.24  4846.5 2145.35  4867.0 2134.90  4877.2 2134.13  4887.5 2140.97
  4895.5 2140.33  4900.6 2136.12  4928.4 2132.05  4944.1 2128.07  4969.4 2126.70
  4979.7 2118.11  4985.6 2117.16  4985.9 2116.66  4989.6 2117.16  4992.8 2117.27
  4996.9 2127.63  5010.1 2129.36  5020.1 2128.76  5050.2 2129.79  5081.6 2137.81
  5100.3 2146.54  5110.3 2148.06  5120.3 2147.02  5170.4 2152.29  5191.7 2153.44
#Mann=5,-1,0
  4782.6    0.07       0  4837.9    0.16       0  4985.6    0.07       0
  4989.6    0.16       0  5081.6    0.07       0
Bank Sta=4985.6,4989.6
Exp/Cntr=0.3,0.1

Type RM Length L Ch R = 1,1278,86,86,86
BEGIN DESCRIPTION:
Elm 77 1278.14
END DESCRIPTION:
XS GIS Cut Line= 3
      1531912.12      6762339.03      1532063.20      6762385.92
      1532291.23      6762394.98
#Sta/Elev= 30
  4843.4 2165.29  4867.4 2163.92  4886.8 2160.71  4892.0 2160.69  4909.2 2155.15
  4919.4 2149.35  4924.6 2148.73  4930.2 2143.96  4951.1 2132.04  4957.2 2127.38
  4962.4 2125.60  5005.0 2125.86  5013.4 2121.49  5021.4 2116.12  5021.7 2115.62
  5025.2 2115.62  5025.4 2116.12  5033.4 2116.42  5043.4 2125.68  5053.4 2130.13
  5063.4 2131.61  5073.4 2131.41  5117.9 2135.87  5143.5 2137.40  5153.5 2140.93
  5179.2 2142.27  5184.2 2142.16  5203.6 2144.90  5213.6 2147.14  5229.8 2148.97
#Mann=4,-1,0
  4843.4    0.16       0  5021.4    0.07       0  5025.4    0.16       0
  5117.9    0.07       0
Bank Sta=5021.4,5025.4
Exp/Cntr=0.3,0.1

Type RM Length L Ch R = 1,1192,72,72,72
BEGIN DESCRIPTION:
Elm 77 1191.62
END DESCRIPTION:
XS GIS Cut Line= 3
      1531877.03      6762432.80      1532060.60      6762471.85
      1532275.47      6762461.44
#Sta/Elev= 30
  4817.1 2172.60  4868.7 2166.38  4886.6 2161.83  4907.0 2153.72  4913.2 2150.22
  4918.3 2151.94  4927.5 2144.90  4957.6 2127.71  4962.8 2127.73  4968.4 2123.25
  4978.6 2121.87  4988.8 2118.17  5002.5 2115.64  5002.7 2115.14  5006.5 2115.64
  5019.2 2115.76  5029.2 2121.86  5039.2 2123.80  5049.2 2129.68  5059.2 2131.81
  5069.3 2131.82  5099.3 2139.37  5109.3 2139.33  5129.3 2136.93  5139.3 2138.12
  5159.4 2144.21  5186.0 2147.55  5199.4 2147.76  5212.2 2149.78  5219.9 2150.31
#Mann=4,-1,0
  4817.1    0.16       0  5002.5    0.07       0  5006.5    0.16       0
  5212.2    0.07       0
Bank Sta=5002.5,5006.5
Exp/Cntr=0.3,0.1

Type RM Length L Ch R = 1,1120,94,94,94
BEGIN DESCRIPTION:
Elm 77 1119.66
END DESCRIPTION:
XS GIS Cut Line= 3
      1531912.16      6762517.43      1532059.30      6762543.47
      1532236.39      6762530.45
#Sta/Elev= 30
  4854.3 2168.06  4867.3 2167.82  4884.4 2165.80  4897.8 2164.97  4908.0 2163.45
  4918.1 2159.26  4928.3 2151.15  4938.4 2144.33  4943.6 2137.82  4948.7 2138.78
  4958.7 2132.85  4968.9 2127.54  4989.2 2118.60  4997.7 2115.18  5005.3 2114.71
  5005.5 2114.21  5009.0 2114.21  5009.3 2114.71  5019.5 2114.82  5029.5 2115.76
  5039.5 2121.72  5049.6 2124.52  5059.6 2127.66  5069.6 2133.31  5079.6 2137.89
  5089.7 2139.33  5109.7 2141.07  5139.8 2142.63  5159.8 2144.34  5181.3 2145.01
#Mann=3,-1,0
  4854.3    0.16       0  5005.3    0.07       0  5009.3    0.16       0
Bank Sta=5005.3,5009.3
Exp/Cntr=0.3,0.1

Type RM Length L Ch R = 1,1026,123,123,123
BEGIN DESCRIPTION:
Elm 77 1026.34
END DESCRIPTION:
XS GIS Cut Line= 3
      1531903.08      6762579.94      1532055.39      6762637.22
      1532201.94      6762634.65
#Sta/Elev= 30
  4842.1 2158.86  4850.1 2159.12  4855.5 2156.81  4875.0 2157.39  4880.4 2153.82
  4897.6 2152.75  4905.3 2150.91  4910.6 2147.39  4929.6 2139.72  4935.5 2134.94
  4940.8 2133.96  4960.4 2125.00  4965.7 2124.15  4972.4 2118.07  4981.0 2114.30
  4981.3 2113.80  4984.8 2113.80  4985.0 2114.30  4996.0 2114.38  5001.9 2115.66
  5007.1 2115.66  5014.4 2118.71  5024.4 2120.06  5034.4 2120.36  5044.4 2126.18
  5074.4 2130.17  5124.5 2134.47  5134.5 2136.15  5144.5 2139.12  5151.4 2142.64
#Mann=3,-1,0
  4842.1    0.16       0  4981.0    0.07       0  4985.0    0.16       0
Bank Sta=4981,4985
Exp/Cntr=0.3,0.1

Type RM Length L Ch R = 1,903,138,138,138
BEGIN DESCRIPTION:
Elm 77 902.56
END DESCRIPTION:
XS GIS Cut Line= 3
      1531847.05      6762693.21      1532003.31      6762745.29
      1532125.71      6762842.95
#Sta/Elev= 30
  4842.4 2164.23  4861.3 2160.05  4870.0 2156.78  4875.3 2156.16  4882.4 2153.33
  4892.9 2150.37  4914.0 2141.85  4924.6 2138.72  4933.2 2134.25  4945.6 2124.24
  4956.2 2118.50  4964.9 2115.97  4970.1 2115.28  4999.7 2113.53  5000.0 2113.03
  5003.5 2113.03  5003.7 2113.53  5011.4 2113.64  5017.6 2116.72  5024.0 2118.11
  5032.0 2122.89  5038.4 2124.04  5046.4 2127.15  5060.4 2131.24  5067.2 2132.41
  5073.6 2135.03  5096.0 2141.35  5116.8 2143.69  5124.4 2145.15  5163.7 2147.24
#Mann=3,-1,0
  4842.4    0.16       0  4999.7    0.07       0  5003.7    0.16       0
Bank Sta=4999.7,5003.7
Exp/Cntr=0.3,0.1

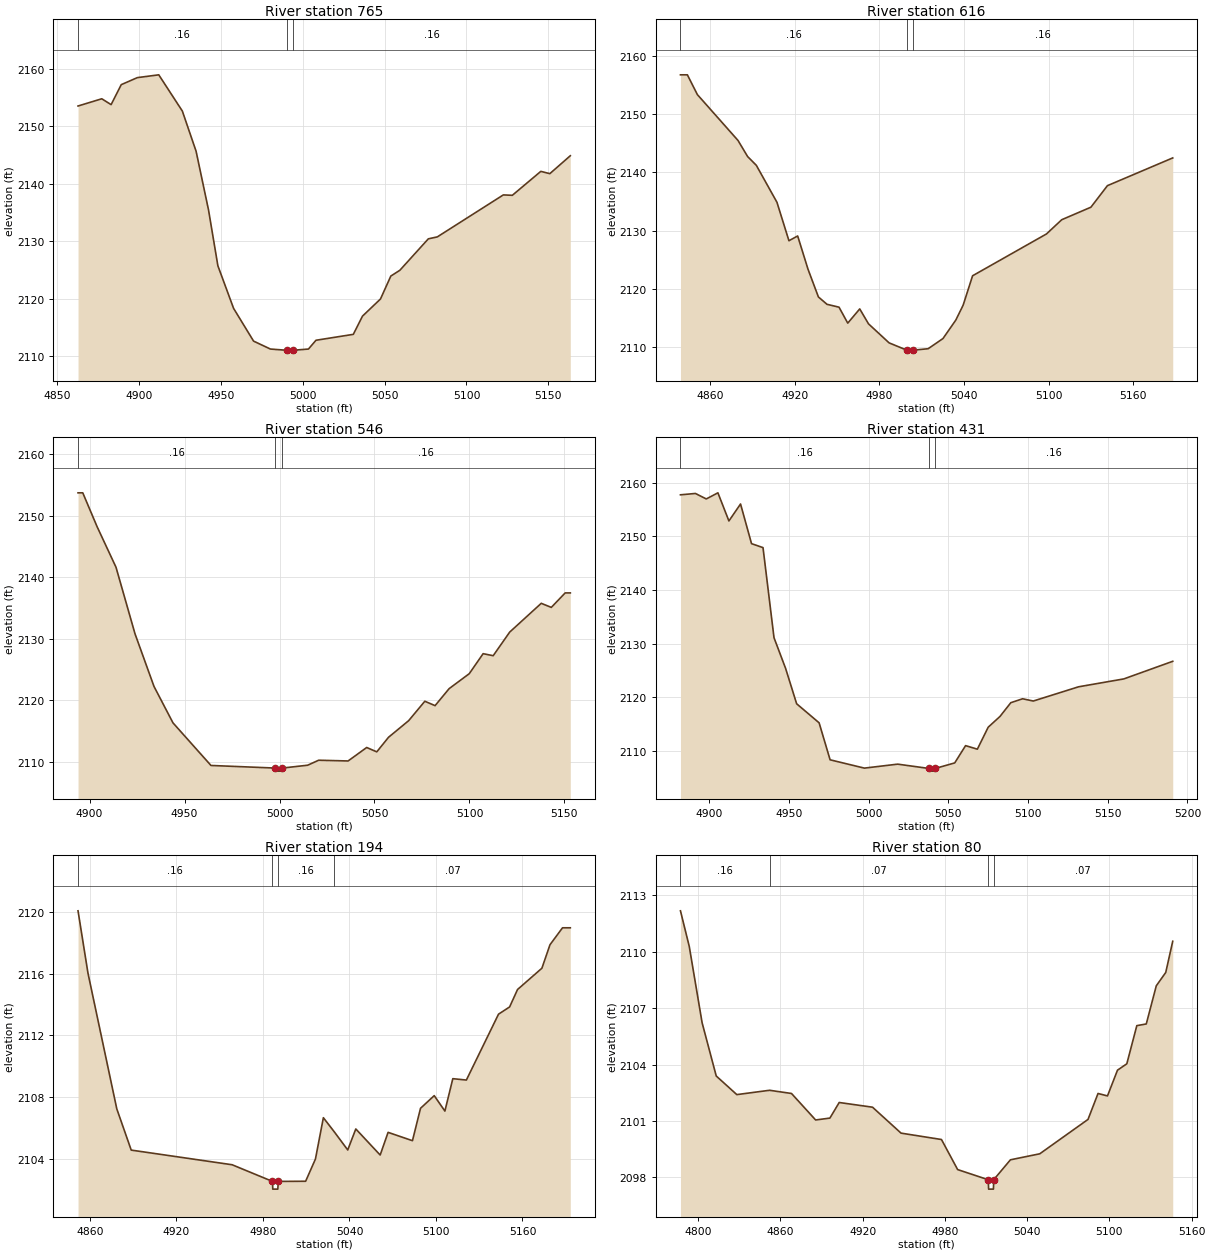
Type RM Length L Ch R = 1,765,149,149,149
BEGIN DESCRIPTION:
Elm 77 764.88
END DESCRIPTION:
XS GIS Cut Line= 3
      1531811.90      6762793.47      1531931.69      6762859.87
      1532080.07      6762928.86
#Sta/Elev= 30
  4862.8 2153.56  4877.3 2154.82  4883.0 2153.80  4889.2 2157.28  4899.0 2158.50
  4912.1 2158.99  4926.5 2152.68  4934.9 2145.68  4942.5 2135.44  4948.2 2125.74
  4957.8 2118.32  4970.0 2112.62  4980.3 2111.24  4990.1 2111.03  4990.4 2110.53
  4994.1 2111.03  5003.5 2111.24  5008.1 2112.77  5030.9 2113.80  5036.5 2116.97
  5047.5 2119.96  5053.8 2123.95  5059.3 2124.95  5076.7 2130.43  5082.2 2130.77
  5122.5 2138.08  5128.0 2138.01  5145.4 2142.18  5150.9 2141.78  5163.4 2144.90
#Mann=3,-1,0
  4862.8    0.16       0  4990.1    0.07       0  4994.1    0.16       0
Bank Sta=4990.1,4994.1
Exp/Cntr=0.3,0.1

Type RM Length L Ch R = 1,616,70,70,70
BEGIN DESCRIPTION:
Elm 77 616.22
END DESCRIPTION:
XS GIS Cut Line= 3
      1531722.05      6762884.61      1531857.47      6762983.57
      1532030.33      6763038.16
#Sta/Elev= 30
  4838.9 2156.83  4843.8 2156.83  4850.9 2153.42  4879.7 2145.52  4886.5 2142.75
  4892.7 2141.23  4907.3 2134.87  4915.8 2128.24  4922.0 2129.06  4929.3 2123.35
  4936.7 2118.55  4942.8 2117.28  4951.3 2116.79  4957.5 2114.04  4966.0 2116.49
  4972.2 2113.92  4986.8 2110.64  4999.5 2109.37  4999.8 2108.87  5003.5 2109.37
  5014.5 2109.63  5025.0 2111.38  5034.1 2114.56  5039.3 2117.13  5046.0 2122.20
  5098.4 2129.41  5109.2 2131.86  5129.9 2134.02  5141.6 2137.73  5187.9 2142.51
#Mann=3,-1,0
  4838.9    0.16       0  4999.5    0.07       0  5003.5    0.16       0
Bank Sta=4999.5,5003.5
Exp/Cntr=0.3,0.1

Type RM Length L Ch R = 1,546,115,115,115
BEGIN DESCRIPTION:
Elm 77 545.979
END DESCRIPTION:
XS GIS Cut Line= 3
      1531705.00      6763038.00      1531811.08      6763035.80
      1531955.01      6763088.00
#Sta/Elev= 30
  4893.9 2153.70  4896.4 2153.70  4903.9 2148.23  4913.9 2141.61  4923.9 2130.80
  4933.9 2122.25  4943.9 2116.33  4963.9 2109.41  4997.5 2108.99  4997.7 2108.49
  5001.2 2108.49  5001.5 2108.99  5014.8 2109.45  5020.6 2110.26  5036.1 2110.14
  5045.9 2112.33  5051.2 2111.62  5057.4 2113.99  5068.0 2116.69  5076.5 2119.84
  5081.9 2119.13  5089.3 2121.89  5099.9 2124.32  5107.2 2127.57  5112.5 2127.24
  5121.2 2131.08  5137.8 2135.75  5143.1 2135.09  5150.4 2137.44  5153.1 2137.44
#Mann=3,-1,0
  4893.9    0.16       0  4997.5    0.07       0  5001.5    0.16       0
Bank Sta=4997.5,5001.5
Exp/Cntr=0.3,0.1

Type RM Length L Ch R = 1,431,237,237,237
BEGIN DESCRIPTION:
Elm 77 4670
END DESCRIPTION:
XS GIS Cut Line= 3
      1531679.99      6763049.97      1531761.10      6763135.81
      1531889.99      6763276.50
#Sta/Elev= 30
  4881.9 2157.76  4891.3 2158.01  4898.1 2156.99  4905.4 2158.13  4912.3 2152.89
  4919.6 2156.05  4926.5 2148.66  4933.7 2147.92  4940.6 2131.14  4947.9 2125.40
  4954.8 2118.83  4968.9 2115.28  4975.8 2108.39  4997.3 2106.84  5018.2 2107.58
  5037.8 2106.78  5038.1 2106.28  5041.6 2106.28  5041.8 2106.78  5054.0 2107.81
  5060.8 2111.03  5068.2 2110.37  5075.0 2114.46  5082.4 2116.47  5089.2 2119.03
  5096.6 2119.76  5103.3 2119.34  5131.7 2121.99  5160.1 2123.46  5190.8 2126.74
#Mann=3,-1,0
  4881.9    0.16       0  5037.8    0.07       0  5041.8    0.16       0
Bank Sta=5037.8,5041.8
Exp/Cntr=0.3,0.1

Type RM Length L Ch R = 1,194,114,114,114
BEGIN DESCRIPTION:
Elm 77 4667
END DESCRIPTION:
XS GIS Cut Line= 3
      1531623.10      6763171.11      1531622.23      6763319.40
      1531707.72      6763492.66
#Sta/Elev= 30
  4851.7 2120.07  4858.6 2116.03  4878.6 2107.23  4888.6 2104.56  4958.6 2103.61
  4986.6 2102.53  4986.8 2102.03  4990.3 2102.03  4990.6 2102.53  5009.6 2102.54
  5016.4 2103.98  5021.9 2106.66  5029.5 2105.74  5038.8 2104.57  5044.4 2105.93
  5061.3 2104.24  5066.8 2105.71  5083.7 2105.17  5089.3 2107.27  5098.8 2108.09
  5106.2 2107.09  5111.7 2109.19  5121.1 2109.10  5143.4 2113.37  5151.1 2113.84
  5156.6 2114.97  5173.5 2116.35  5179.1 2117.87  5187.8 2118.97  5193.2 2118.97
#Mann=4,-1,0
  4851.7    0.16       0  4986.6    0.07       0  4990.6    0.16       0
  5029.5    0.07       0
Bank Sta=4986.6,4990.6
Exp/Cntr=0.3,0.1

Type RM Length L Ch R = 1,80,0,0,0
BEGIN DESCRIPTION:
Elm 77 4666
END DESCRIPTION:
XS GIS Cut Line= 3
      1531590.55      6763182.77      1531535.14      6763388.33
      1531641.31      6763488.83
#Sta/Elev= 30
  4787.1 2112.18  4793.5 2110.29  4802.9 2106.22  4813.2 2103.39  4828.2 2102.40
  4852.1 2102.63  4868.1 2102.46  4885.7 2101.05  4896.1 2101.15  4902.9 2101.98
  4927.2 2101.73  4948.0 2100.35  4977.5 2100.01  4989.3 2098.41  5011.6 2097.87
  5011.9 2097.37  5015.4 2097.37  5015.6 2097.87  5027.8 2098.93  5049.2 2099.25
  5084.4 2101.08  5091.7 2102.46  5098.6 2102.33  5105.9 2103.70  5112.7 2104.04
  5120.0 2106.07  5126.9 2106.16  5134.2 2108.19  5141.1 2108.90  5146.2 2110.56
#Mann=4,-1,0
  4787.1    0.16       0  4852.1    0.07       0  5011.6    0.07       0
  5015.6    0.07       0
Bank Sta=5011.6,5015.6
Exp/Cntr=0.3,0.1

Chan Stop Cuts=-1