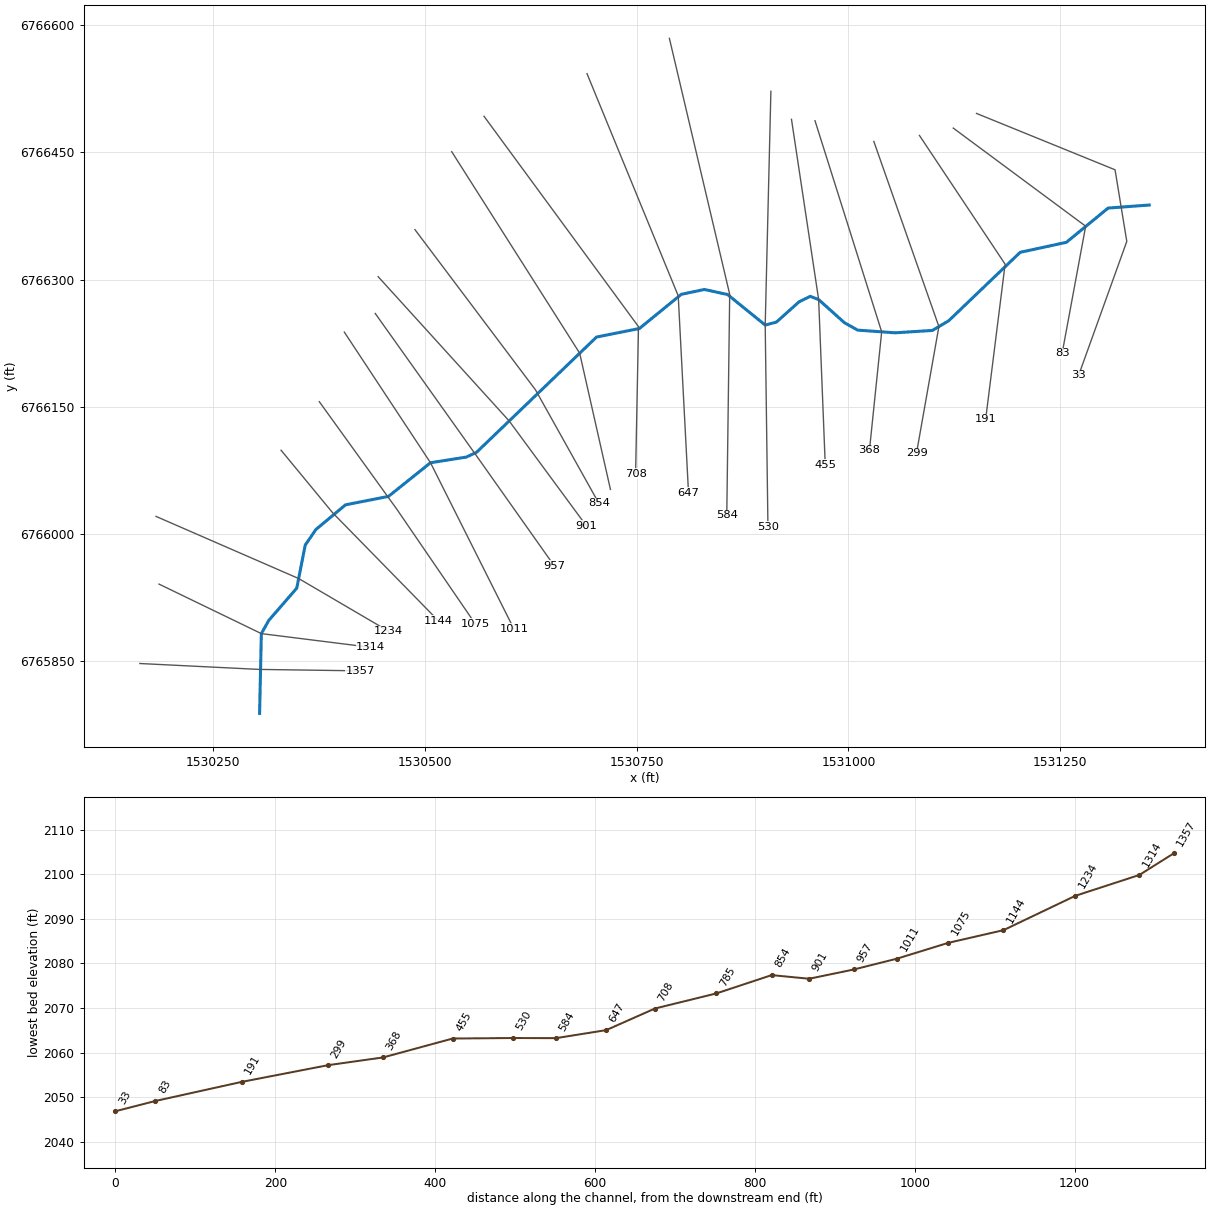
--- Elm 78.prj (project) ---

Proj Title=Elm 78 Base Level Engineering
Current Plan=p01
Default Exp/Contr=0.3,0.1
English Units
Geom File=g01
Flow File=f01
Plan File=p01
BEGIN DESCRIPTION:
Elm 78
END DESCRIPTION:

--- Elm 78.p01 (plan) ---

Plan Title=Multiple Run
Short Identifier=Multiple
Geom File=g01
Flow File=f01
Subcritical Flow
K Sum by GR= 0
Std Step Tol= 0.01
Critical Tol= 0.01
Num of Std Step Trials= 20
Max Error Tol= 0.3
Flow Tol Ratio= 0.001
Split Flow NTrial= 30
Split Flow Tol= 0.02
Split Flow Ratio= 0.02
Log Output Level= 0
Friction Slope Method= 1
Unsteady Friction Slope Method= 2
Unsteady Bridges Friction Slope Method= 1
Parabolic Critical Depth
Global Vel Dist=  1 , 1 , 1
Global Log Level= 0
CheckData=True
Encroach Param= -1, 0, 0, 0
BEGIN DESCRIPTION:
Multiple Run
END DESCRIPTION:

--- Elm 78.f01 (steady flow) ---

Flow Title=Multiple
Number of Profiles=7
Profile Names=10-year,25-year,50-year,1pct_min,100-year,1pct_plu,500-year
River Rch & RM= Elm 78,Reach-1,1357
      34      42      47      33      53      74      69
Boundary for River Rch & Prof#=Elm 78,Reach-1,1
Up Type=0
Dn Type=3
Dn Slope=0.005
Boundary for River Rch & Prof#=Elm 78,Reach-1,2
Up Type=0
Dn Type=3
Dn Slope=0.005
Boundary for River Rch & Prof#=Elm 78,Reach-1,3
Up Type=0
Dn Type=3
Dn Slope=0.005
Boundary for River Rch & Prof#=Elm 78,Reach-1,4
Up Type=0
Dn Type=3
Dn Slope=0.005
Boundary for River Rch & Prof#=Elm 78,Reach-1,5
Up Type=0
Dn Type=3
Dn Slope=0.005
Boundary for River Rch & Prof#=Elm 78,Reach-1,6
Up Type=0
Dn Type=3
Dn Slope=0.005
Boundary for River Rch & Prof#=Elm 78,Reach-1,7
Up Type=0
Dn Type=3
Dn Slope=0.005

--- Elm 78.g01 (geometry) ---

Geom Title=Existing Conditions

River Reach=Elm 78,Reach-1
Reach XY= 30
      1530305.00      6765788.00      1530307.07      6765882.14
      1530315.79      6765897.67      1530348.88      6765935.84
      1530358.85      6765986.58      1530371.48      6766005.06
      1530406.42      6766034.14      1530457.16      6766044.11
      1530506.73      6766083.81      1530548.96      6766090.50
      1530561.06      6766096.14      1530702.70      6766232.17
      1530753.26      6766242.25      1530802.81      6766282.64
      1530830.03      6766288.33      1530857.30      6766282.37
      1530901.77      6766246.32      1530915.04      6766249.85
      1530941.63      6766273.66      1530954.90      6766280.20
      1530964.85      6766276.38      1530995.21      6766249.14
      1531010.89      6766240.35      1531055.00      6766237.18
      1531099.10      6766239.97      1531118.29      6766251.36
      1531202.70      6766332.17      1531257.24      6766343.97
      1531306.49      6766384.40      1531355.00      6766388.00

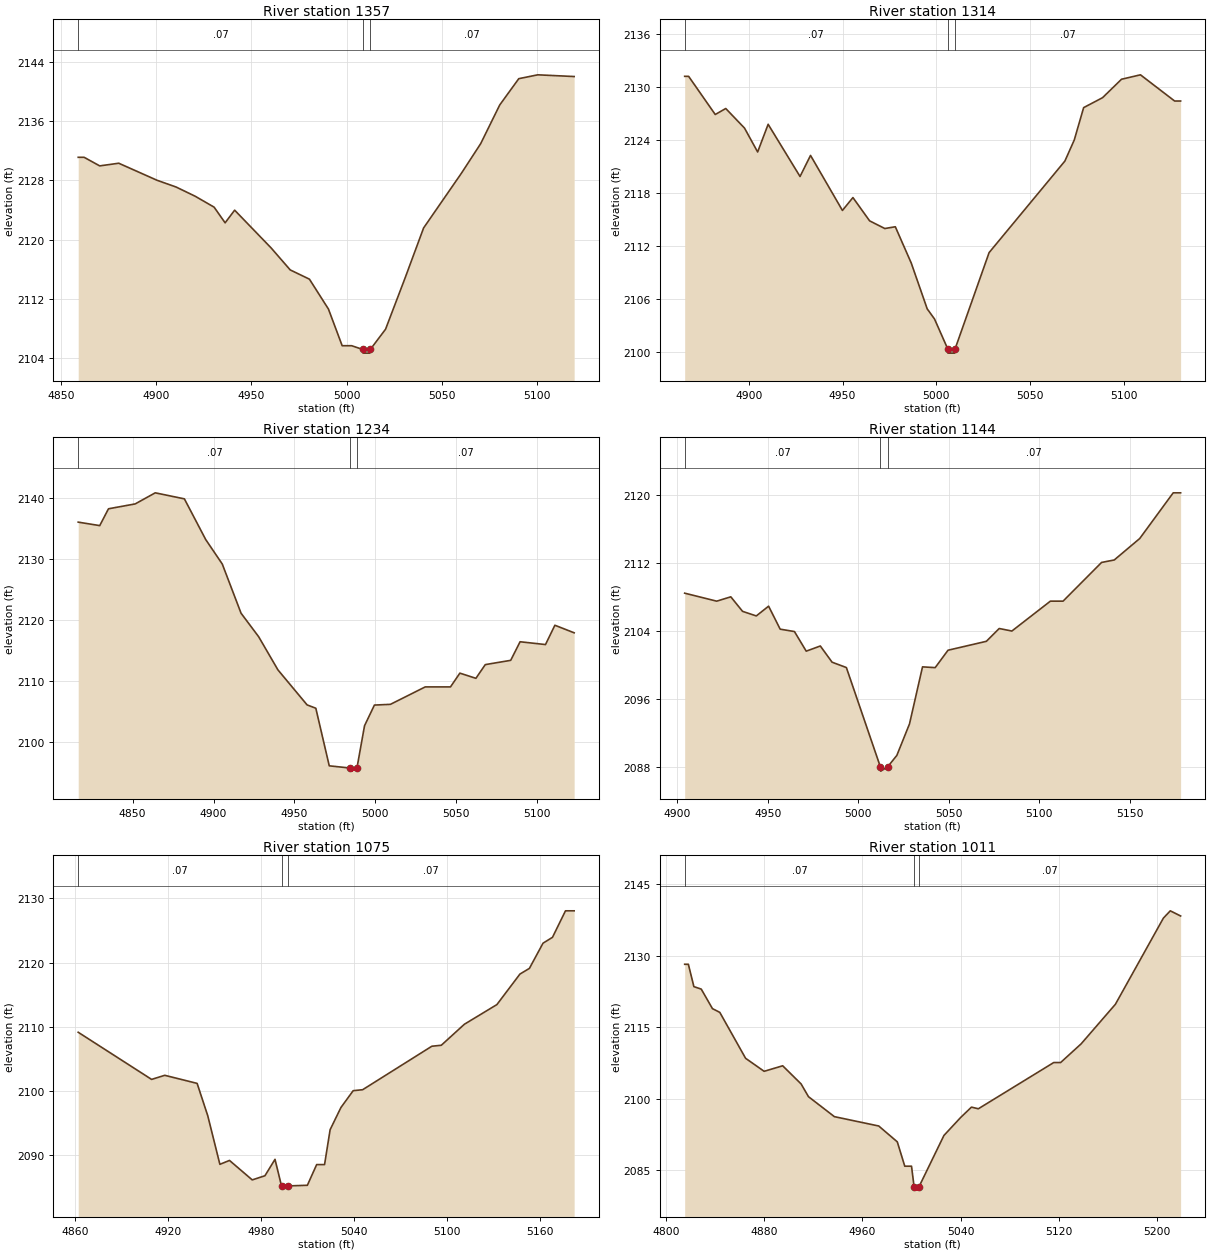
Type RM Length L Ch R = 1,1357,43,43,43
BEGIN DESCRIPTION:
Elm 78 4749
END DESCRIPTION:
XS GIS Cut Line= 3
      1530163.70      6765846.85      1530304.52      6765839.89
      1530424.11      6765838.17
#Sta/Elev= 29
  4859.0 2131.13  4862.1 2131.13  4870.3 2129.97  4880.3 2130.33  4900.4 2128.03
  4910.4 2127.12  4920.4 2125.88  4930.4 2124.40  4936.2 2122.28  4941.2 2123.99
  4960.4 2118.88  4970.4 2115.92  4980.5 2114.67  4990.5 2110.63  4997.7 2105.68
  5002.7 2105.68  5008.5 2105.18  5008.7 2104.68  5012.2 2104.68  5012.5 2105.18
  5020.5 2107.91  5030.5 2114.65  5040.5 2121.59  5060.5 2129.03  5070.5 2132.98
  5080.5 2138.20  5090.5 2141.75  5100.5 2142.27  5119.6 2142.04
#Mann=3,-1,0
  4859.0    0.07       0  5008.5    0.07       0  5012.5    0.07       0
Bank Sta=5008.5,5012.5
Exp/Cntr=0.3,0.1

Type RM Length L Ch R = 1,1314,80,80,80
BEGIN DESCRIPTION:
Elm 78 4750
END DESCRIPTION:
XS GIS Cut Line= 3
      1530186.27      6765940.59      1530307.07      6765882.14
      1530436.26      6765865.95
#Sta/Elev= 30
  4865.8 2131.23  4867.9 2131.23  4882.1 2126.90  4887.7 2127.58  4897.7 2125.36
  4904.7 2122.65  4910.3 2125.79  4927.3 2119.87  4932.9 2122.26  4949.9 2116.02
  4955.5 2117.48  4964.4 2114.84  4972.5 2113.97  4978.1 2114.17  4986.6 2110.05
  4995.1 2104.86  4999.0 2103.71  5006.0 2100.34  5006.2 2099.84  5009.7 2099.84
  5010.0 2100.34  5028.1 2111.24  5068.5 2121.62  5073.5 2124.01  5078.5 2127.68
  5088.6 2128.81  5098.7 2130.90  5108.8 2131.40  5127.0 2128.43  5130.2 2128.43
#Mann=3,-1,0
  4865.8    0.07       0  5006.0    0.07       0  5010.0    0.07       0
Bank Sta=5006,5010
Exp/Cntr=0.3,0.1

Type RM Length L Ch R = 1,1234,90,90,90
BEGIN DESCRIPTION:
Elm 78 4751
END DESCRIPTION:
XS GIS Cut Line= 3
      1530182.77      6766020.47      1530351.10      6765947.16
      1530457.05      6765885.07
#Sta/Elev= 30
  4816.4 2136.03  4829.7 2135.46  4835.1 2138.22  4851.6 2139.02  4864.0 2140.84
  4882.0 2139.85  4895.2 2133.16  4905.4 2129.16  4917.0 2121.09  4927.9 2117.22
  4939.8 2111.78  4957.8 2106.04  4963.2 2105.49  4971.5 2096.04  4984.6 2095.67
  4984.9 2095.17  4988.6 2095.67  4993.3 2102.62  4999.4 2106.01  5009.3 2106.13
  5030.8 2108.99  5046.4 2108.99  5052.2 2111.25  5062.1 2110.40  5067.9 2112.65
  5083.6 2113.35  5089.4 2116.40  5105.1 2115.94  5110.9 2119.11  5122.8 2117.87
#Mann=3,-1,0
  4816.4    0.07       0  4984.6    0.07       0  4988.6    0.07       0
Bank Sta=4984.6,4988.6
Exp/Cntr=0.3,0.1

Type RM Length L Ch R = 1,1144,69,69,69
BEGIN DESCRIPTION:
Elm 78 4748
END DESCRIPTION:
XS GIS Cut Line= 3
      1530330.35      6766098.59      1530391.43      6766024.53
      1530516.11      6765897.20
#Sta/Elev= 30
  4904.0 2108.42  4921.7 2107.48  4929.5 2107.99  4936.0 2106.28  4943.6 2105.74
  4950.4 2106.89  4956.8 2104.18  4964.7 2103.90  4971.2 2101.59  4979.0 2102.20
  4985.5 2100.29  4993.4 2099.66  5012.2 2087.96  5012.4 2087.46  5016.2 2087.96
  5021.3 2089.31  5028.3 2093.02  5035.5 2099.74  5042.5 2099.65  5049.6 2101.70
  5070.8 2102.75  5077.9 2104.26  5084.9 2103.96  5106.2 2107.48  5113.2 2107.48
  5134.5 2112.04  5141.5 2112.33  5155.6 2114.86  5174.1 2120.24  5178.2 2120.24
#Mann=3,-1,0
  4904.0    0.07       0  5012.2    0.07       0  5016.2    0.07       0
Bank Sta=5012.2,5016.2
Exp/Cntr=0.3,0.1

Type RM Length L Ch R = 1,1075,64,64,64
BEGIN DESCRIPTION:
Elm 78 4747
END DESCRIPTION:
XS GIS Cut Line= 3
      1530375.49      6766155.87      1530466.98      6766028.95
      1530559.51      6765893.73
#Sta/Elev= 30
  4862.0 2109.11  4909.4 2101.75  4917.9 2102.39  4938.8 2101.13  4945.7 2096.05
  4953.5 2088.49  4959.7 2089.10  4974.4 2086.06  4982.6 2086.71  4989.1 2089.27
  4993.3 2085.12  4993.5 2084.62  4997.3 2085.12  5010.0 2085.22  5016.0 2088.45
  5021.1 2088.45  5024.7 2093.90  5031.7 2097.37  5039.6 2099.99  5045.7 2100.14
  5090.4 2106.93  5096.5 2107.08  5111.4 2110.36  5132.4 2113.43  5147.3 2118.20
  5153.4 2119.08  5162.2 2123.02  5168.3 2123.93  5176.7 2128.07  5182.3 2128.07
#Mann=3,-1,0
  4862.0    0.07       0  4993.3    0.07       0  4997.3    0.07       0
Bank Sta=4993.3,4997.3
Exp/Cntr=0.3,0.1

Type RM Length L Ch R = 1,1011,54,54,54
BEGIN DESCRIPTION:
Elm 78 1010.792
END DESCRIPTION:
XS GIS Cut Line= 3
      1530405.01      6766237.98      1530506.73      6766083.81
      1530605.01      6765887.99
#Sta/Elev= 30
  4815.3 2128.24  4818.3 2128.24  4822.8 2123.55  4828.8 2123.03  4837.9 2118.94
  4843.9 2118.15  4864.9 2108.52  4880.0 2105.79  4895.1 2106.95  4910.1 2103.14
  4916.1 2100.47  4937.2 2096.28  4973.3 2094.32  4988.4 2091.00  4994.5 2085.89
  5000.0 2085.89  5002.1 2081.58  5002.3 2081.08  5006.1 2081.58  5026.4 2092.34
  5040.1 2096.13  5048.8 2098.28  5054.4 2097.93  5115.8 2107.63  5121.4 2107.63
  5138.1 2111.55  5166.0 2119.85  5205.1 2137.93  5210.7 2139.45  5219.1 2138.37
#Mann=3,-1,0
  4815.3    0.07       0  5002.1    0.07       0  5006.1    0.07       0
Bank Sta=5002.1,5006.1
Exp/Cntr=0.3,0.1

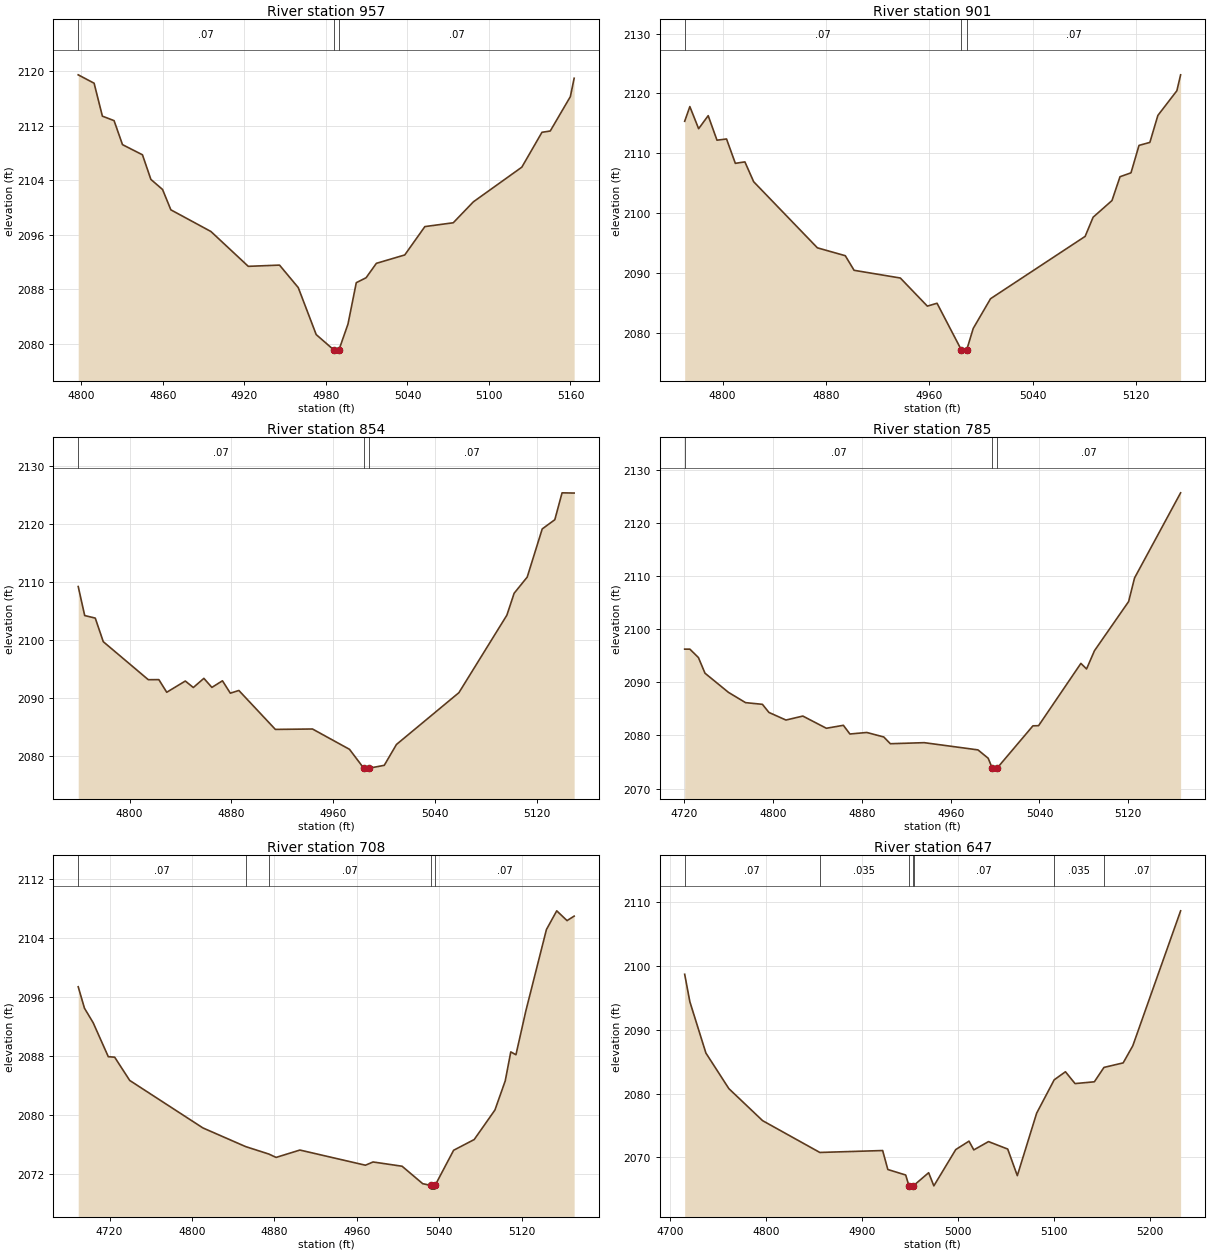
Type RM Length L Ch R = 1,957,56,56,56
BEGIN DESCRIPTION:
Elm 78 957.18
END DESCRIPTION:
XS GIS Cut Line= 3
      1530441.48      6766260.02      1530561.25      6766091.64
      1530652.71      6765962.23
#Sta/Elev= 30
  4797.6 2119.47  4809.3 2118.24  4815.4 2113.41  4824.0 2112.75  4830.2 2109.23
  4844.9 2107.74  4851.1 2104.13  4859.7 2102.65  4865.8 2099.67  4895.3 2096.49
  4922.8 2091.38  4945.8 2091.56  4959.6 2088.26  4972.8 2081.37  4985.6 2079.15
  4985.8 2078.65  4989.6 2079.15  4996.2 2082.91  5002.3 2088.98  5009.5 2089.70
  5017.1 2091.82  5038.0 2093.05  5052.8 2097.21  5073.7 2097.77  5088.5 2100.84
  5124.2 2105.93  5139.0 2111.04  5145.1 2111.23  5159.9 2116.27  5162.7 2118.97
#Mann=3,-1,0
  4797.6    0.07       0  4985.6    0.07       0  4989.6    0.07       0
Bank Sta=4985.6,4989.6
Exp/Cntr=0.3,0.1

Type RM Length L Ch R = 1,901,47,47,47
BEGIN DESCRIPTION:
Elm 78 901.24
END DESCRIPTION:
XS GIS Cut Line= 3
      1530444.95      6766303.43      1530599.44      6766133.31
      1530690.74      6766009.29
#Sta/Elev= 30
  4770.7 2115.34  4774.7 2117.80  4781.5 2114.10  4788.9 2116.28  4795.7 2112.18
  4803.1 2112.38  4809.9 2108.31  4817.3 2108.55  4824.1 2105.23  4873.4 2094.18
  4895.0 2092.86  4901.8 2090.42  4937.6 2089.13  4958.5 2084.43  4966.0 2084.91
  4984.9 2077.07  4985.2 2076.57  4988.9 2077.07  4994.0 2080.70  5007.4 2085.67
  5080.6 2096.09  5086.8 2099.30  5101.4 2102.09  5107.6 2106.07  5116.1 2106.72
  5122.3 2111.31  5130.7 2111.81  5136.9 2116.32  5151.6 2120.45  5154.5 2123.11
#Mann=3,-1,0
  4770.7    0.07       0  4984.9    0.07       0  4988.9    0.07       0
Bank Sta=4984.9,4988.9
Exp/Cntr=0.3,0.1

Type RM Length L Ch R = 1,854,69,69,69
BEGIN DESCRIPTION:
Elm 78 854.38
END DESCRIPTION:
XS GIS Cut Line= 3
      1530488.36      6766358.97      1530630.69      6766169.77
      1530705.36      6766036.06
#Sta/Elev= 30
  4759.6 2109.24  4764.7 2104.23  4773.0 2103.79  4779.3 2099.72  4814.7 2093.16
  4823.0 2093.17  4829.2 2090.99  4843.8 2092.93  4850.1 2091.81  4858.4 2093.39
  4864.7 2091.83  4873.0 2092.97  4879.2 2090.83  4885.9 2091.30  4914.6 2084.58
  4943.8 2084.65  4972.9 2081.14  4984.1 2077.88  4984.3 2077.38  4988.1 2077.88
  5000.2 2078.38  5009.8 2081.98  5058.9 2090.92  5096.6 2104.29  5102.3 2108.07
  5112.6 2110.87  5124.4 2119.18  5134.3 2120.77  5140.0 2125.41  5149.5 2125.37
#Mann=3,-1,0
  4759.6    0.07       0  4984.1    0.07       0  4988.1    0.07       0
Bank Sta=4984.1,4988.1
Exp/Cntr=0.3,0.1

Type RM Length L Ch R = 1,785,77,77,77
BEGIN DESCRIPTION:
Elm 78 785.38
END DESCRIPTION:
XS GIS Cut Line= 3
      1530531.76      6766450.98      1530682.78      6766213.17
      1530719.10      6766052.33
#Sta/Elev= 30
  4720.5 2096.25  4725.2 2096.25  4732.9 2094.66  4738.8 2091.72  4760.0 2088.10
  4775.3 2086.18  4790.5 2085.86  4796.4 2084.33  4811.7 2082.90  4826.9 2083.65
  4848.1 2081.35  4863.4 2081.91  4869.3 2080.27  4884.5 2080.56  4899.8 2079.71
  4905.7 2078.44  4936.2 2078.64  4984.6 2077.28  4993.8 2075.71  4997.6 2073.78
  4997.9 2073.28  5001.6 2073.78  5034.1 2081.81  5039.2 2081.84  5077.3 2093.57
  5082.4 2092.52  5089.5 2095.95  5120.3 2105.22  5125.6 2109.65  5167.1 2125.69
#Mann=3,-1,0
  4720.5    0.07       0  4997.6    0.07       0  5001.6    0.07       0
Bank Sta=4997.6,5001.6
Exp/Cntr=0.3,0.1

Type RM Length L Ch R = 1,708,61,61,61
BEGIN DESCRIPTION:
Elm 78 707.75
END DESCRIPTION:
XS GIS Cut Line= 3
      1530569.93      6766492.69      1530752.22      6766244.42
      1530748.79      6766071.07
#Sta/Elev= 30
  4689.6 2097.39  4695.7 2094.47  4704.1 2092.51  4718.8 2087.89  4725.0 2087.82
  4739.6 2084.66  4810.6 2078.21  4852.1 2075.67  4874.6 2074.66  4881.7 2074.20
  4904.8 2075.20  4968.4 2073.14  4975.8 2073.58  5004.0 2073.00  5024.0 2070.63
  5032.0 2070.39  5032.3 2069.89  5035.8 2069.89  5036.0 2070.39  5054.0 2075.17
  5074.0 2076.63  5094.1 2080.64  5104.1 2084.60  5109.5 2088.54  5114.5 2088.15
  5124.1 2094.10  5144.1 2105.17  5154.1 2107.71  5164.1 2106.38  5171.0 2106.99
#Mann=5,-1,0
  4689.6    0.07       0  4852.1   0.035       0  4874.6    0.07       0
  5032.0    0.07       0  5036.0    0.07       0
Bank Sta=5032,5036
Exp/Cntr=0.3,0.1

Type RM Length L Ch R = 1,647,63,63,63
BEGIN DESCRIPTION:
Elm 78 647.43
END DESCRIPTION:
XS GIS Cut Line= 3
      1530691.46      6766543.02      1530799.10      6766280.88
      1530811.25      6766048.28
#Sta/Elev= 30
  4715.4 2098.67  4720.8 2094.37  4737.5 2086.34  4761.4 2080.77  4796.5 2075.76
  4856.1 2070.78  4921.5 2071.08  4926.9 2068.11  4945.5 2067.25  4948.9 2065.54
  4949.1 2065.04  4952.9 2065.54  4953.7 2065.59  4969.4 2067.61  4974.8 2065.55
  4997.6 2071.23  5011.4 2072.55  5016.4 2071.18  5031.7 2072.48  5051.7 2071.31
  5061.7 2067.15  5081.8 2076.92  5100.1 2082.15  5111.8 2083.41  5121.8 2081.56
  5141.9 2081.84  5151.9 2084.09  5171.9 2084.80  5181.9 2087.47  5231.7 2108.60
#Mann=7,-1,0
  4715.4    0.07       0  4856.1   0.035       0  4948.9    0.07       0
  4952.9   0.035       0  4953.7    0.07       0  5100.1   0.035       0
  5151.9    0.07       0
Bank Sta=4948.9,4952.9
Exp/Cntr=0.3,0.1

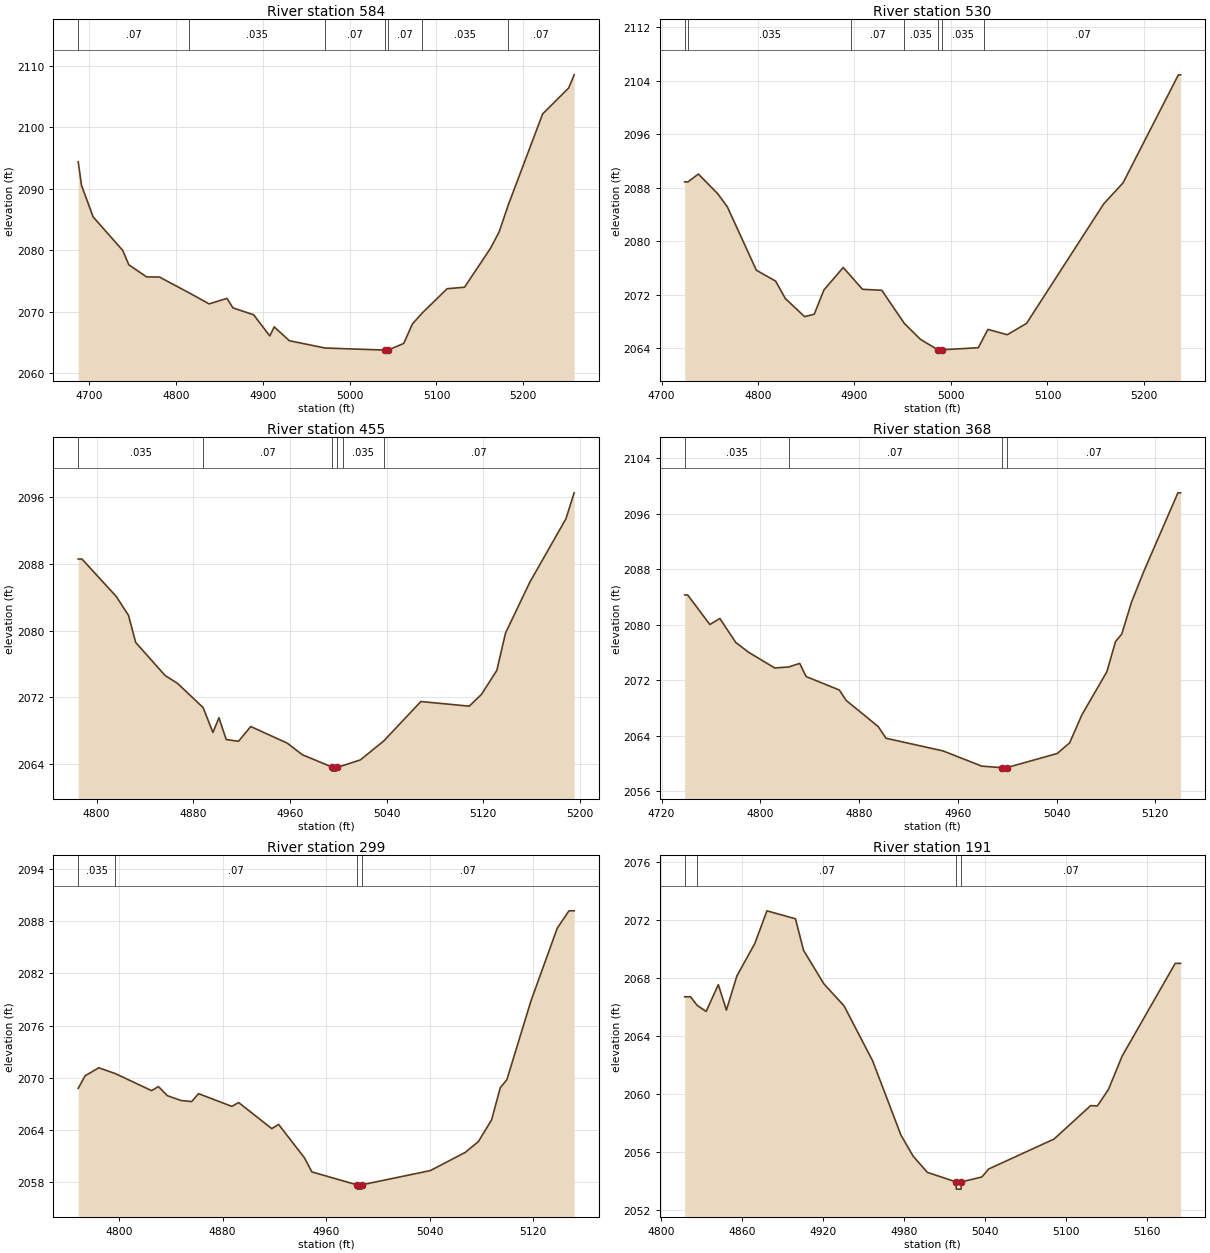
Type RM Length L Ch R = 1,584,54,54,54
BEGIN DESCRIPTION:
Elm 78 583.74
END DESCRIPTION:
XS GIS Cut Line= 3
      1530788.67      6766584.74      1530859.86      6766282.62
      1530856.41      6766021.74
#Sta/Elev= 30
  4687.3 2094.38  4691.1 2090.54  4704.5 2085.40  4738.6 2079.95  4745.6 2077.61
  4766.1 2075.64  4780.9 2075.62  4815.2 2073.04  4838.1 2071.25  4858.6 2072.15
  4865.6 2070.60  4889.4 2069.48  4908.0 2066.03  4913.1 2067.51  4930.5 2065.26
  4971.7 2064.07  5040.3 2063.74  5040.6 2063.24  5044.3 2063.74  5062.3 2064.82
  5072.3 2067.99  5083.9 2069.81  5112.3 2073.72  5132.3 2073.96  5162.3 2080.31
  5172.3 2083.00  5182.7 2087.34  5222.3 2102.16  5252.3 2106.38  5258.6 2108.52
#Mann=7,-1,0
  4687.3    0.07       0  4815.2   0.035       0  4971.7    0.07       0
  5040.3    0.07       0  5044.3    0.07       0  5083.9   0.035       0
  5182.7    0.07       0
Bank Sta=5040.3,5044.3
Exp/Cntr=0.3,0.1

Type RM Length L Ch R = 1,530,75,75,75
BEGIN DESCRIPTION:
Elm 78 529.752
END DESCRIPTION:
XS GIS Cut Line= 3
      1530908.47      6766522.24      1530901.77      6766246.32
      1530905.00      6766008.34
#Sta/Elev= 30
  4724.0 2088.86  4727.4 2088.86  4738.2 2090.03  4758.2 2087.10  4768.2 2085.14
  4798.3 2075.66  4818.3 2074.03  4828.3 2071.43  4848.3 2068.72  4858.3 2069.09
  4868.3 2072.71  4888.3 2076.07  4896.7 2074.70  4908.3 2072.81  4928.3 2072.66
  4951.6 2067.72  4968.3 2065.34  4986.3 2063.77  4986.6 2063.27  4990.1 2063.27
  4990.3 2063.77  5028.3 2064.08  5034.6 2065.81  5038.3 2066.82  5058.3 2066.02
  5078.3 2067.71  5158.3 2085.58  5178.3 2088.71  5235.7 2104.86  5238.0 2104.86
#Mann=7,-1,0
  4724.0    0.07       0  4727.4   0.035       0  4896.7    0.07       0
  4951.6   0.035       0  4986.3   0.035       0  4990.3   0.035       0
  5034.6    0.07       0
Bank Sta=4986.3,4990.3
Exp/Cntr=0.3,0.1

Type RM Length L Ch R = 1,455,87,87,87
BEGIN DESCRIPTION:
Elm 78 4738
END DESCRIPTION:
XS GIS Cut Line= 3
      1530932.78      6766489.18      1530964.85      6766276.38
      1530972.64      6766081.24
#Sta/Elev= 30
  4784.8 2088.60  4787.9 2088.60  4816.3 2084.11  4826.4 2081.85  4832.4 2078.59
  4856.8 2074.62  4866.9 2073.70  4888.2 2070.78  4896.3 2067.80  4901.3 2069.56
  4907.3 2066.95  4917.5 2066.74  4927.6 2068.51  4957.9 2066.51  4970.3 2065.13
  4994.7 2063.66  4994.9 2063.16  4998.4 2063.16  4998.7 2063.66  5003.8 2063.82
  5018.4 2064.51  5037.8 2066.79  5068.4 2071.51  5108.5 2070.95  5118.5 2072.35
  5131.3 2075.24  5138.5 2079.72  5158.5 2085.79  5188.5 2093.43  5195.3 2096.54
#Mann=6,-1,0
  4784.8   0.035       0  4888.2    0.07       0  4994.7    0.07       0
  4998.7    0.07       0  5003.8   0.035       0  5037.8    0.07       0
Bank Sta=4994.7,4998.7
Exp/Cntr=0.3,0.1

Type RM Length L Ch R = 1,368,69,69,69
BEGIN DESCRIPTION:
Elm 78 4737
END DESCRIPTION:
XS GIS Cut Line= 3
      1530960.55      6766487.49      1531039.24      6766238.31
      1531024.79      6766098.56
#Sta/Elev= 30
  4738.7 2084.32  4741.1 2084.32  4759.1 2080.05  4767.2 2080.92  4780.1 2077.46
  4790.6 2076.04  4811.6 2073.79  4823.0 2073.93  4831.9 2074.45  4837.1 2072.55
  4864.0 2070.61  4869.5 2069.12  4895.5 2065.34  4901.8 2063.66  4947.9 2061.84
  4979.4 2059.64  4995.5 2059.42  4995.8 2058.92  4999.3 2058.92  4999.5 2059.42
  5040.5 2061.46  5050.6 2063.00  5060.6 2067.06  5080.7 2073.23  5087.8 2077.61
  5092.8 2078.67  5100.8 2083.32  5110.9 2087.80  5138.3 2099.03  5140.5 2099.03
#Mann=4,-1,0
  4738.7   0.035       0  4823.0    0.07       0  4995.5    0.07       0
  4999.5    0.07       0
Bank Sta=4995.5,4999.5
Exp/Cntr=0.3,0.1

Type RM Length L Ch R = 1,299,108,108,108
BEGIN DESCRIPTION:
Elm 78 4736
END DESCRIPTION:
XS GIS Cut Line= 3
      1531029.99      6766463.03      1531106.77      6766244.52
      1531080.35      6766095.14
#Sta/Elev= 30
  4768.4 2068.77  4773.7 2070.21  4784.3 2071.14  4797.2 2070.46  4825.1 2068.51
  4830.4 2068.98  4837.3 2067.93  4847.9 2067.37  4856.1 2067.25  4861.4 2068.16
  4887.1 2066.70  4892.4 2067.14  4918.0 2064.14  4923.3 2064.62  4943.3 2060.77
  4949.0 2059.16  4983.7 2057.68  4984.0 2057.18  4987.5 2057.18  4987.7 2057.68
  5040.5 2059.31  5067.6 2061.41  5077.7 2062.65  5087.9 2065.15  5094.6 2068.84
  5099.7 2069.77  5118.3 2078.82  5138.6 2087.18  5147.7 2089.19  5151.7 2089.19
#Mann=4,-1,0
  4768.4   0.035       0  4797.2    0.07       0  4983.7    0.07       0
  4987.7    0.07       0
Bank Sta=4983.7,4987.7
Exp/Cntr=0.3,0.1

Type RM Length L Ch R = 1,191,108,108,108
BEGIN DESCRIPTION:
Elm 78 4735
END DESCRIPTION:
XS GIS Cut Line= 3
      1531083.82      6766470.11      1531184.93      6766318.17
      1531161.94      6766135.01
#Sta/Elev= 30
  4817.5 2066.72  4821.8 2066.72  4826.8 2066.12  4833.4 2065.71  4842.4 2067.56
  4848.4 2065.80  4856.1 2068.15  4869.4 2070.40  4878.4 2072.66  4899.5 2072.11
  4905.5 2069.93  4920.5 2067.62  4935.5 2066.09  4956.6 2062.30  4977.6 2057.16
  4986.6 2055.71  4997.1 2054.59  5018.3 2053.93  5018.6 2053.43  5022.1 2053.43
  5022.3 2053.93  5037.5 2054.27  5042.5 2054.82  5090.9 2056.89  5118.0 2059.20
  5123.0 2059.18  5131.2 2060.32  5141.3 2062.62  5180.6 2069.03  5184.6 2069.03
#Mann=4,-1,0
  4817.5   0.035       0  4826.8    0.07       0  5018.3    0.07       0
  5022.3    0.07       0
Bank Sta=5018.3,5022.3
Exp/Cntr=0.3,0.1

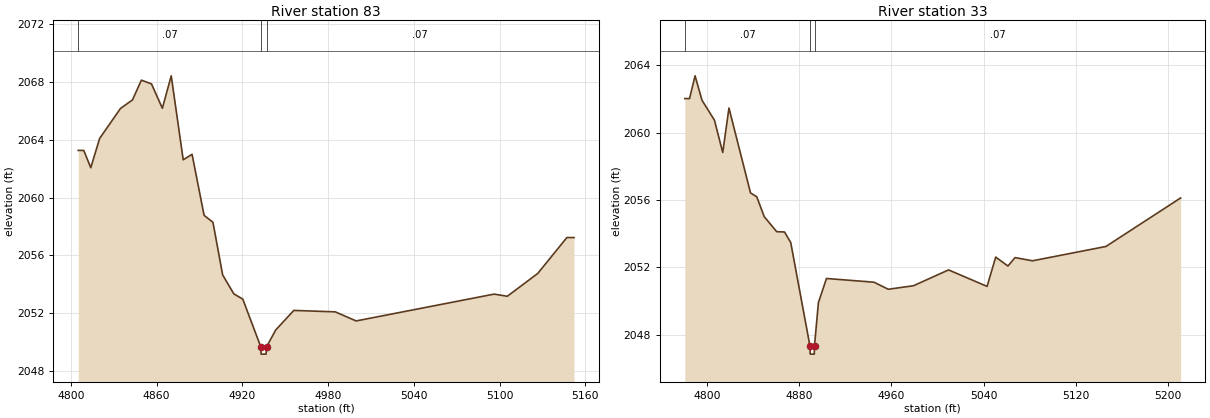
Type RM Length L Ch R = 1,83,50,50,50
BEGIN DESCRIPTION:
Elm 78 4734
END DESCRIPTION:
XS GIS Cut Line= 3
      1531123.74      6766478.80      1531280.00      6766363.00
      1531252.23      6766213.04
#Sta/Elev= 30
  4805.1 2063.27  4809.0 2063.27  4813.9 2062.07  4820.1 2064.10  4834.7 2066.18
  4843.1 2066.77  4849.3 2068.14  4856.4 2067.88  4864.0 2066.19  4870.2 2068.44
  4878.6 2062.62  4884.8 2063.00  4893.2 2058.77  4899.4 2058.29  4906.2 2054.64
  4914.0 2053.33  4920.3 2052.96  4932.9 2049.65  4933.1 2049.15  4936.6 2049.15
  4936.9 2049.65  4943.3 2050.82  4956.0 2052.18  4985.0 2052.08  4999.6 2051.45
  5096.2 2053.31  5105.4 2053.16  5126.7 2054.74  5147.1 2057.23  5152.1 2057.23
#Mann=3,-1,0
  4805.1    0.07       0  4932.9    0.07       0  4936.9    0.07       0
Bank Sta=4932.9,4936.9
Exp/Cntr=0.3,0.1

Type RM Length L Ch R = 1,33,0,0,0
BEGIN DESCRIPTION:
aaaaa2
END DESCRIPTION:
XS GIS Cut Line= 4
      1531151.18      6766496.10      1531314.69      6766429.59
      1531328.54      6766345.06      1531271.71      6766187.04
#Sta/Elev= 30
  4780.9 2062.02  4785.0 2062.02  4789.8 2063.37  4795.8 2061.92  4806.6 2060.74
  4813.8 2058.82  4819.2 2061.46  4837.9 2056.42  4843.3 2056.19  4849.8 2055.01
  4860.6 2054.12  4867.4 2054.10  4872.8 2053.47  4889.4 2047.35  4889.7 2046.85
  4893.2 2046.85  4893.4 2047.35  4896.8 2049.91  4903.8 2051.34  4945.0 2051.12
  4957.4 2050.70  4979.3 2050.91  5009.7 2051.85  5043.1 2050.87  5050.6 2052.61
  5061.2 2052.08  5067.4 2052.58  5082.5 2052.39  5146.2 2053.24  5211.0 2056.12
#Mann=3,-1,0
  4780.9    0.07       0  4889.4    0.07       0  4893.4    0.07       0
Bank Sta=4889.4,4893.4
Exp/Cntr=0.3,0.1

Chan Stop Cuts=-1