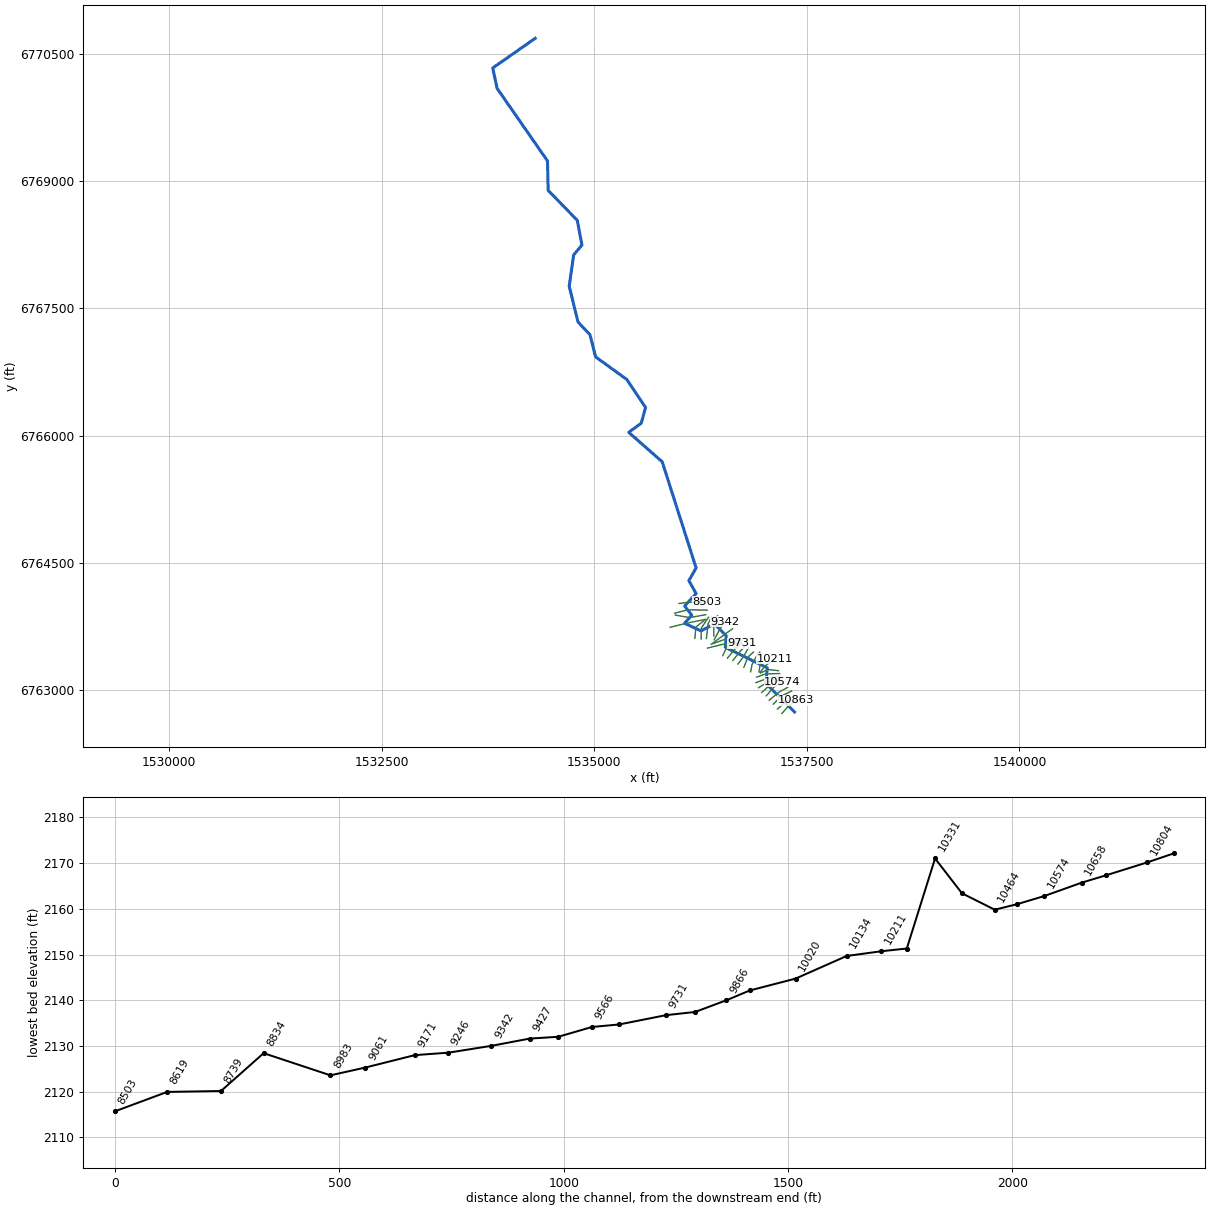
--- Elm 79.prj (project) ---

Proj Title=Elm 79 Base Level Engineering
Current Plan=p01
Default Exp/Contr=0.3,0.1
English Units
Geom File=g01
Flow File=f01
Plan File=p01
BEGIN DESCRIPTION:
Elm 79
END DESCRIPTION:

--- Elm 79.p01 (plan) ---

Plan Title=Multiple Run
Short Identifier=Multiple
Geom File=g01
Flow File=f01
Subcritical Flow
K Sum by GR= 0
Std Step Tol= 0.01
Critical Tol= 0.01
Num of Std Step Trials= 20
Max Error Tol= 0.3
Flow Tol Ratio= 0.001
Split Flow NTrial= 30
Split Flow Tol= 0.02
Split Flow Ratio= 0.02
Log Output Level= 0
Friction Slope Method= 1
Unsteady Friction Slope Method= 2
Unsteady Bridges Friction Slope Method= 1
Parabolic Critical Depth
Global Vel Dist=  1 , 1 , 1
Global Log Level= 0
CheckData=True
Encroach Param= -1, 0, 0, 0
BEGIN DESCRIPTION:
Multiple Run
END DESCRIPTION:

--- Elm 79.f01 (steady flow) ---

Flow Title=Multiple
Number of Profiles=7
Profile Names=10-year,25-year,50-year,1pct_min,100-year,1pct_plu,500-year
River Rch & RM= Elm 79,Reach-1,10863
     199     279     346     269     431     592     671
River Rch & RM= Elm 79,Reach-1,8834
     264     374     468     365     584     804     921
River Rch & RM= Elm 79,Reach-1,7268
     316     452     569     445     714     982    1140
River Rch & RM= Elm 79,Reach-1,5856
     385     555     703     552     885    1220    1420
River Rch & RM= Elm 79,Reach-1,2528
     405     585     741     582     933    1280    1500
River Rch & RM= Elm 79,Reach-1,553
     440     638     810     638    1020    1410    1650
Boundary for River Rch & Prof#=Elm 79,Reach-1,1
Up Type=0
Dn Type=3
Dn Slope=0.005
Boundary for River Rch & Prof#=Elm 79,Reach-1,2
Up Type=0
Dn Type=3
Dn Slope=0.005
Boundary for River Rch & Prof#=Elm 79,Reach-1,3
Up Type=0
Dn Type=3
Dn Slope=0.005
Boundary for River Rch & Prof#=Elm 79,Reach-1,4
Up Type=0
Dn Type=3
Dn Slope=0.005
Boundary for River Rch & Prof#=Elm 79,Reach-1,5
Up Type=0
Dn Type=3
Dn Slope=0.005
Boundary for River Rch & Prof#=Elm 79,Reach-1,6
Up Type=0
Dn Type=3
Dn Slope=0.005
Boundary for River Rch & Prof#=Elm 79,Reach-1,7
Up Type=0
Dn Type=3
Dn Slope=0.005

--- Elm 79.g01 (geometry) ---

Geom Title=Existing Conditions

River Reach=Elm 79,Reach-1
Reach XY= 30
      1537355.00      6762738.00      1537016.10      6763077.68
      1537035.63      6763258.09      1536540.88      6763501.39
      1536551.84      6763636.35      1536414.68      6763777.83
      1536255.09      6763695.28      1536061.97      6763784.67
      1536146.01      6763881.33      1536062.10      6763988.00
      1536197.23      6764134.59      1536112.50      6764288.00
      1536197.47      6764437.99      1535798.95      6765690.19
      1535405.00      6766038.00      1535551.93      6766146.30
      1535603.48      6766331.61      1535382.28      6766661.89
      1535015.47      6766928.18      1534949.17      6767190.30
      1534808.54      6767339.47      1534704.60      6767763.00
      1534757.07      6768132.14      1534854.40      6768248.62
      1534799.53      6768540.45      1534456.96      6768893.89
      1534449.53      6769240.45      1533856.23      6770098.51
      1533805.00      6770338.00      1534305.00      6770688.00

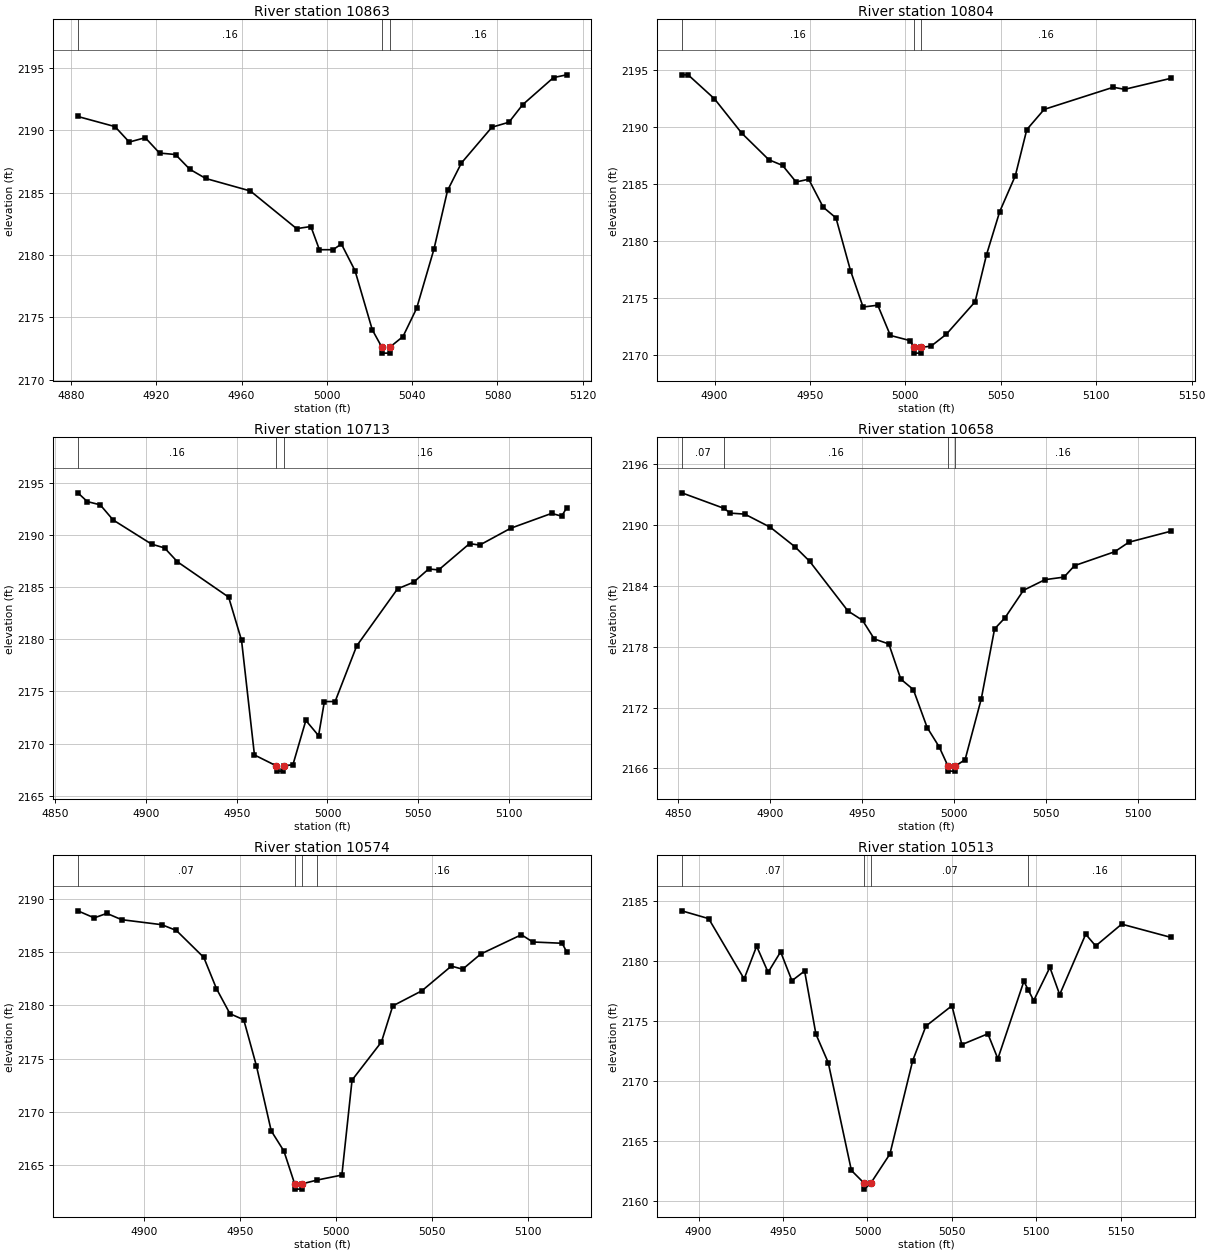
Type RM Length L Ch R = 1,10863,59,59,59
BEGIN DESCRIPTION:
Elm 79 4029
END DESCRIPTION:
XS GIS Cut Line= 3
      1537207.10      6762721.48      1537285.39      6762808.16
      1537373.78      6762877.75
#Sta/Elev= 30
  4883.2 2191.10  4900.6 2190.29  4907.3 2189.05  4914.8 2189.40  4921.5 2188.17
  4929.0 2188.05  4935.7 2186.87  4943.2 2186.13  4964.1 2185.13  4985.8 2182.11
  4992.5 2182.28  4996.5 2180.42  5002.9 2180.42  5006.8 2180.88  5013.2 2178.74
  5021.3 2174.00  5025.7 2172.63  5025.9 2172.13  5029.4 2172.13  5029.7 2172.63
  5035.7 2173.46  5042.1 2175.72  5050.2 2180.45  5056.6 2185.17  5063.1 2187.37
  5077.4 2190.24  5085.4 2190.64  5091.8 2192.04  5106.3 2194.22  5112.5 2194.44
#Mann=3,-1,0
  4883.2    0.16       0  5025.7    0.07       0  5029.7    0.16       0
Bank Sta=5025.7,5029.7
Exp/Cntr=0.3,0.1

Type RM Length L Ch R = 1,10804,91,91,91
BEGIN DESCRIPTION:
Elm 79 4028
END DESCRIPTION:
XS GIS Cut Line= 3
      1537155.01      6762773.56      1537243.74      6762850.14
      1537359.95      6762926.40
#Sta/Elev= 30
  4882.8 2194.55  4886.1 2194.55  4899.9 2192.45  4914.2 2189.44  4928.4 2187.11
  4935.6 2186.61  4942.7 2185.16  4949.3 2185.40  4956.9 2182.95  4963.6 2182.01
  4971.2 2177.40  4977.8 2174.20  4985.5 2174.36  4992.1 2171.71  5002.6 2171.25
  5004.4 2170.66  5004.6 2170.16  5008.1 2170.16  5008.4 2170.66  5013.5 2170.78
  5021.4 2171.81  5036.5 2174.66  5042.5 2178.79  5049.4 2182.56  5057.6 2185.71
  5063.6 2189.75  5072.7 2191.52  5108.9 2193.46  5114.9 2193.28  5139.0 2194.24
#Mann=3,-1,0
  4882.8    0.16       0  5004.4    0.07       0  5008.4    0.16       0
Bank Sta=5004.4,5008.4
Exp/Cntr=0.3,0.1

Type RM Length L Ch R = 1,10713,55,55,55
BEGIN DESCRIPTION:
Elm 79 4027
END DESCRIPTION:
XS GIS Cut Line= 3
      1537104.71      6762830.89      1537202.39      6762927.52
      1537320.88      6762985.00
#Sta/Elev= 30
  4862.6 2194.04  4867.8 2193.20  4874.9 2192.89  4882.0 2191.44  4903.2 2189.12
  4910.3 2188.76  4917.4 2187.43  4945.6 2184.04  4952.7 2179.90  4959.8 2168.91
  4971.9 2167.86  4972.2 2167.36  4975.7 2167.36  4975.9 2167.86  4981.0 2167.98
  4988.1 2172.22  4995.1 2170.76  4998.3 2174.03  5004.2 2174.03  5016.1 2179.37
  5038.6 2184.84  5047.4 2185.47  5055.7 2186.74  5061.2 2186.65  5078.2 2189.17
  5083.8 2189.03  5100.8 2190.64  5123.4 2192.07  5128.9 2191.80  5131.7 2192.61
#Mann=3,-1,0
  4862.6    0.16       0  4971.9    0.07       0  4975.9    0.16       0
Bank Sta=4971.9,4975.9
Exp/Cntr=0.3,0.1

Type RM Length L Ch R = 1,10658,84,84,84
BEGIN DESCRIPTION:
Elm 79 4026
END DESCRIPTION:
XS GIS Cut Line= 3
      1537057.85      6762877.78      1537172.08      6762971.58
      1537274.82      6763028.79
#Sta/Elev= 30
  4852.2 2193.17  4875.1 2191.64  4878.5 2191.17  4886.4 2191.07  4900.3 2189.77
  4913.7 2187.84  4921.6 2186.42  4942.4 2181.52  4950.3 2180.60  4956.7 2178.76
  4964.6 2178.27  4971.1 2174.80  4977.9 2173.77  4985.4 2170.03  4991.9 2168.13
  4996.7 2166.23  4996.9 2165.73  5000.4 2165.73  5000.7 2166.23  5006.0 2166.86
  5014.8 2172.87  5022.0 2179.75  5027.7 2180.86  5037.7 2183.56  5049.4 2184.61
  5059.7 2184.86  5065.4 2185.99  5087.2 2187.36  5094.9 2188.30  5117.6 2189.38
#Mann=4,-1,0
  4852.2    0.07       0  4875.1    0.16       0  4996.7    0.07       0
  5000.7    0.16       0
Bank Sta=4996.7,5000.7
Exp/Cntr=0.3,0.1

Type RM Length L Ch R = 1,10574,61,61,61
BEGIN DESCRIPTION:
Elm 79 4025
END DESCRIPTION:
XS GIS Cut Line= 3
      1537023.08      6762928.08      1537111.03      6763029.85
      1537212.64      6763093.87
#Sta/Elev= 30
  4865.5 2188.86  4874.0 2188.20  4880.6 2188.62  4888.3 2188.03  4909.2 2187.56
  4916.8 2187.02  4931.1 2184.49  4937.7 2181.56  4944.7 2179.22  4951.9 2178.65
  4958.5 2174.33  4966.2 2168.24  4972.8 2166.35  4978.4 2163.28  4978.7 2162.78
  4982.2 2162.78  4982.4 2163.28  4990.1 2163.63  5003.0 2164.10  5008.3 2173.00
  5023.6 2176.57  5029.5 2179.95  5044.7 2181.37  5060.0 2183.68  5065.9 2183.39
  5075.3 2184.81  5096.5 2186.62  5102.4 2185.94  5117.7 2185.82  5120.1 2185.01
#Mann=4,-1,0
  4865.5    0.07       0  4978.4    0.07       0  4982.4    0.07       0
  4990.1    0.16       0
Bank Sta=4978.4,4982.4
Exp/Cntr=0.3,0.1

Type RM Length L Ch R = 1,10513,49,49,49
BEGIN DESCRIPTION:
Elm 79 10513.132
END DESCRIPTION:
XS GIS Cut Line= 3
      1536971.00      6762969.76      1537052.17      6763043.86
      1537205.00      6763138.00
#Sta/Elev= 30
  4890.1 2184.21  4906.0 2183.56  4927.0 2178.53  4934.4 2181.26  4941.2 2179.08
  4948.6 2180.79  4955.3 2178.38  4962.8 2179.19  4969.5 2173.92  4976.8 2171.54
  4990.5 2162.55  4998.0 2161.49  4998.2 2160.99  5002.0 2161.49  5013.3 2163.92
  5026.8 2171.72  5034.6 2174.59  5050.0 2176.29  5055.9 2173.05  5071.3 2173.95
  5077.2 2171.87  5092.6 2178.33  5095.1 2177.64  5098.4 2176.72  5108.0 2179.49
  5113.8 2177.22  5129.2 2182.26  5135.1 2181.28  5150.5 2183.10  5179.5 2182.00
#Mann=4,-1,0
  4890.1    0.07       0  4998.0    0.07       0  5002.0    0.07       0
  5095.1    0.16       0
Bank Sta=4998,5002
Exp/Cntr=0.3,0.1

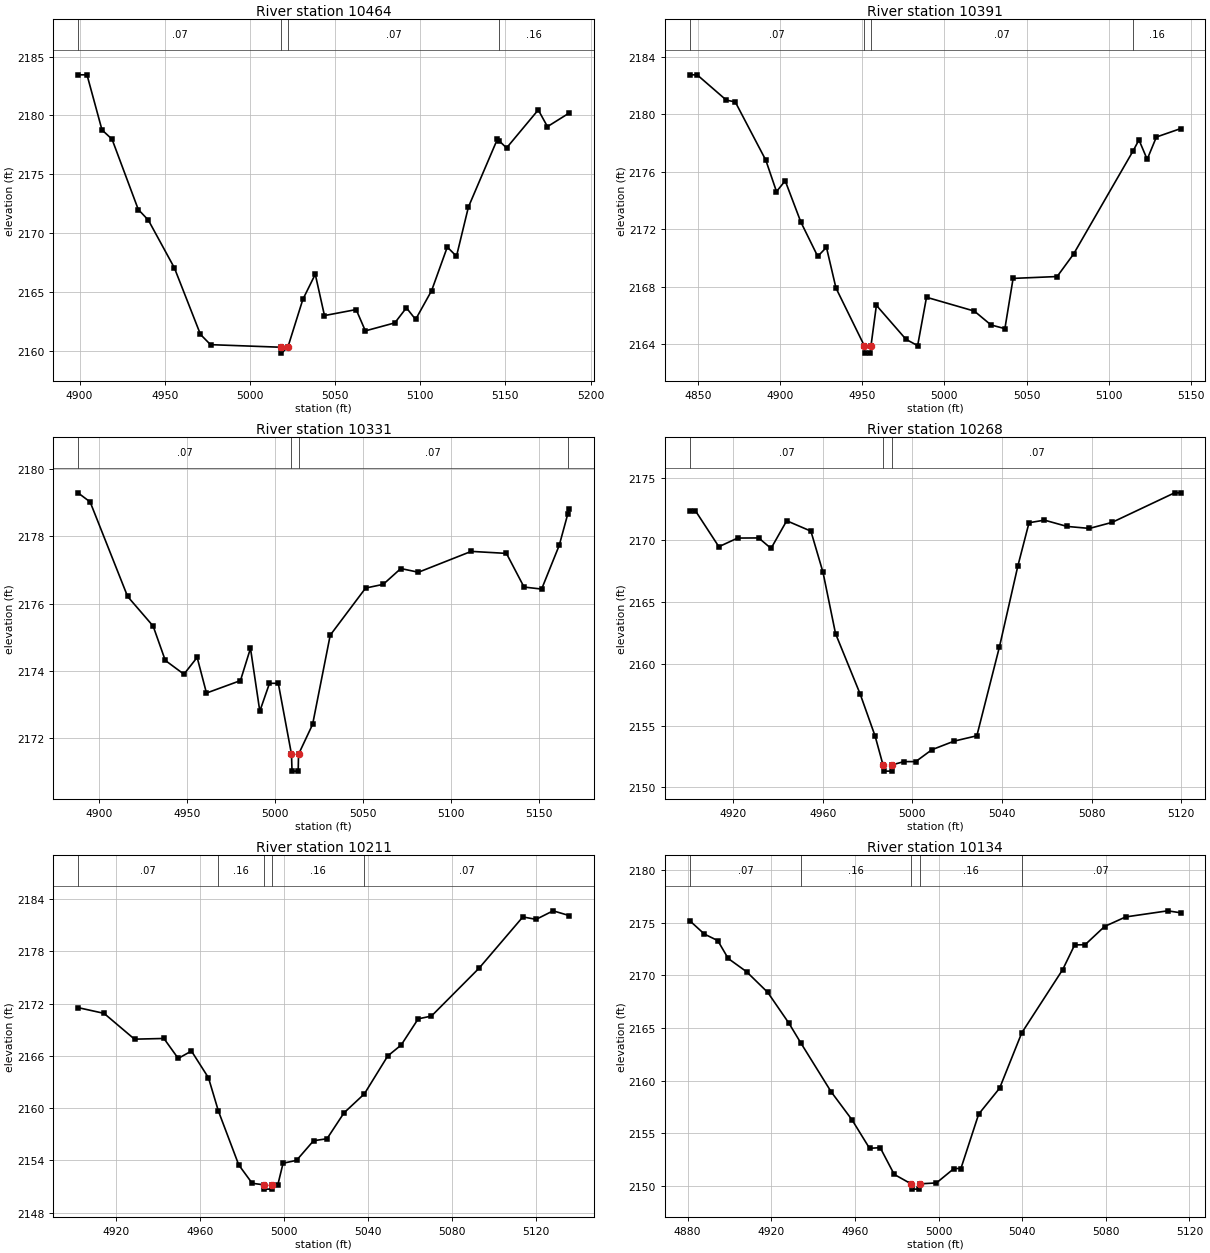
Type RM Length L Ch R = 1,10464,73,73,73
BEGIN DESCRIPTION:
Elm 79 10464.12
END DESCRIPTION:
XS GIS Cut Line= 3
      1536931.06      6763023.58      1537019.63      6763079.15
      1537189.75      6763148.58
#Sta/Elev= 30
  4899.1 2183.45  4904.4 2183.45  4913.2 2178.77  4919.1 2177.98  4934.5 2172.01
  4940.4 2171.11  4955.7 2167.05  4971.0 2161.40  4976.9 2160.53  5018.3 2160.31
  5018.5 2159.81  5022.3 2160.31  5031.1 2164.37  5038.4 2166.51  5043.8 2163.00
  5062.4 2163.51  5067.8 2161.70  5085.1 2162.38  5091.9 2163.66  5097.3 2162.67
  5106.7 2165.12  5115.9 2168.82  5121.3 2168.04  5128.3 2172.22  5145.3 2177.98
  5146.5 2177.82  5150.7 2177.24  5169.3 2180.47  5174.7 2179.05  5187.4 2180.20
#Mann=4,-1,0
  4899.1    0.07       0  5018.3    0.07       0  5022.3    0.07       0
  5146.5    0.16       0
Bank Sta=5018.3,5022.3
Exp/Cntr=0.3,0.1

Type RM Length L Ch R = 1,10391,60,60,60
BEGIN DESCRIPTION:
Elm 79 10390.96
END DESCRIPTION:
XS GIS Cut Line= 3
      1536901.54      6763084.35      1537047.41      6763138.18
      1537189.77      6763155.54
#Sta/Elev= 30
  4845.0 2182.73  4849.5 2182.73  4867.3 2180.97  4872.7 2180.85  4891.3 2176.80
  4897.8 2174.62  4903.1 2175.37  4912.6 2172.51  4922.9 2170.12  4928.2 2170.75
  4934.0 2167.92  4951.3 2163.90  4951.5 2163.40  4955.0 2163.40  4955.3 2163.90
  4958.6 2166.72  4976.6 2164.36  4983.7 2163.92  4989.1 2167.28  5018.2 2166.32
  5028.3 2165.36  5036.8 2165.10  5041.8 2168.59  5068.6 2168.72  5078.6 2170.28
  5114.8 2177.44  5118.4 2178.21  5123.4 2176.86  5129.0 2178.41  5143.9 2179.00
#Mann=4,-1,0
  4845.0    0.07       0  4951.3    0.07       0  4955.3    0.07       0
  5114.8    0.16       0
Bank Sta=4951.3,4955.3
Exp/Cntr=0.3,0.1

Type RM Length L Ch R = 1,10331,63,63,63
BEGIN DESCRIPTION:
Elm 79 10331.08
END DESCRIPTION:
XS GIS Cut Line= 3
      1536908.56      6763148.61      1537010.95      6763186.79
      1537180.59      6763191.98
#Sta/Elev= 30
  4888.1 2179.29  4895.0 2179.02  4916.3 2176.21  4930.8 2175.33  4937.7 2174.31
  4948.3 2173.90  4955.8 2174.40  4961.1 2173.34  4980.4 2173.71  4986.1 2174.67
  4991.4 2172.80  4996.9 2173.63  5001.9 2173.63  5009.4 2171.52  5009.7 2171.02
  5013.2 2171.02  5013.4 2171.52  5021.4 2172.41  5031.4 2175.06  5051.5 2176.46
  5061.5 2176.57  5071.5 2177.04  5081.5 2176.93  5111.5 2177.55  5131.5 2177.49
  5141.5 2176.49  5151.5 2176.43  5161.5 2177.73  5166.4 2178.67  5167.1 2178.80
#Mann=4,-1,0
  4888.1    0.07       0  5009.4    0.07       0  5013.4    0.07       0
  5166.4    0.16       0
Bank Sta=5009.4,5013.4
Exp/Cntr=0.3,0.1

Type RM Length L Ch R = 1,10268,57,57,57
BEGIN DESCRIPTION:
Elm 79 10267.62
END DESCRIPTION:
XS GIS Cut Line= 3
      1536955.43      6763198.96      1537045.67      6763238.87
      1537165.50      6763224.98
#Sta/Elev= 30
  4900.6 2172.39  4903.1 2172.39  4913.6 2169.47  4922.0 2170.17  4931.4 2170.18
  4936.9 2169.33  4943.9 2171.57  4954.7 2170.73  4960.1 2167.40  4965.7 2162.44
  4976.7 2157.55  4983.4 2154.13  4986.9 2151.81  4987.2 2151.31  4990.7 2151.31
  4990.9 2151.81  4996.2 2152.08  5001.5 2152.08  5008.7 2153.04  5018.7 2153.74
  5028.8 2154.17  5038.9 2161.37  5047.1 2167.90  5052.1 2171.41  5059.0 2171.62
  5069.1 2171.11  5079.1 2170.95  5089.2 2171.44  5117.1 2173.83  5119.9 2173.83
#Mann=3,-1,0
  4900.6    0.07       0  4986.9    0.07       0  4990.9    0.07       0
Bank Sta=4986.9,4990.9
Exp/Cntr=0.3,0.1

Type RM Length L Ch R = 1,10211,77,77,77
BEGIN DESCRIPTION:
Elm 79 10210.71
END DESCRIPTION:
XS GIS Cut Line= 3
      1536950.20      6763205.91      1537009.22      6763280.54
      1537118.58      6763365.60
#Sta/Elev= 30
  4902.0 2171.53  4914.4 2170.87  4928.9 2167.91  4942.9 2167.99  4949.7 2165.70
  4956.0 2166.55  4964.1 2163.48  4968.8 2159.68  4978.5 2153.49  4984.9 2151.38
  4990.3 2151.21  4990.6 2150.71  4994.1 2150.71  4994.3 2151.21  4997.1 2151.21
  4999.6 2153.68  5006.0 2154.01  5014.1 2156.26  5020.5 2156.49  5028.6 2159.46
  5038.3 2161.64  5049.4 2165.98  5055.8 2167.24  5063.9 2170.24  5070.2 2170.56
  5092.9 2176.06  5113.7 2181.93  5120.0 2181.65  5128.1 2182.63  5135.7 2182.09
#Mann=5,-1,0
  4902.0    0.07       0  4968.8    0.16       0  4990.3    0.07       0
  4994.3    0.16       0  5038.3    0.07       0
Bank Sta=4990.3,4994.3
Exp/Cntr=0.3,0.1

Type RM Length L Ch R = 1,10134,114,114,114
BEGIN DESCRIPTION:
Elm 79 10134.38
END DESCRIPTION:
XS GIS Cut Line= 3
      1536938.03      6763211.05      1536955.40      6763339.57
      1536945.10      6763444.28
#Sta/Elev= 30
  4881.0 2175.19  4888.0 2173.92  4894.4 2173.30  4899.4 2171.60  4908.2 2170.34
  4918.3 2168.38  4928.4 2165.46  4934.2 2163.55  4948.6 2158.94  4958.6 2156.27
  4967.0 2153.56  4972.1 2153.62  4978.8 2151.08  4986.9 2150.18  4987.2 2149.68
  4990.7 2149.68  4990.9 2150.18  4999.0 2150.27  5007.4 2151.64  5010.7 2151.64
  5019.2 2156.81  5029.2 2159.27  5039.8 2164.53  5059.4 2170.55  5065.1 2172.89
  5070.1 2172.91  5079.4 2174.64  5089.5 2175.55  5109.6 2176.13  5115.9 2175.94
#Mann=5,-1,0
  4881.0    0.07       0  4934.2    0.16       0  4986.9    0.07       0
  4990.9    0.16       0  5039.8    0.07       0
Bank Sta=4986.9,4990.9
Exp/Cntr=0.3,0.1

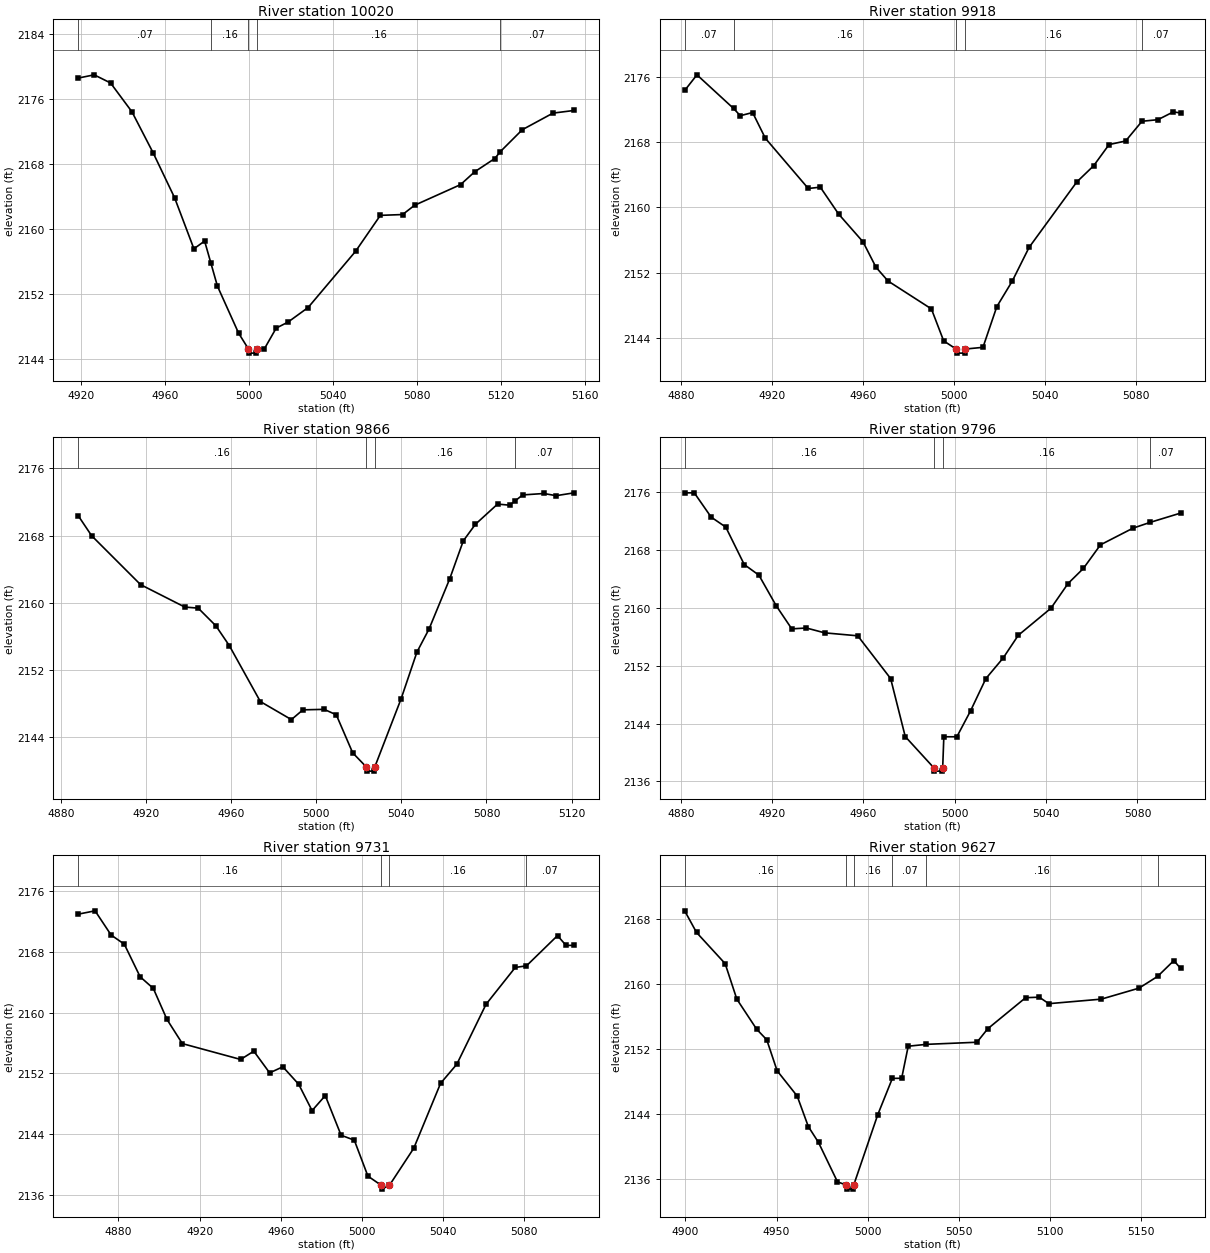
Type RM Length L Ch R = 1,10020,102,102,102
BEGIN DESCRIPTION:
Elm 79 10020.38
END DESCRIPTION:
XS GIS Cut Line= 3
      1536839.08      6763212.86      1536854.70      6763296.17
      1536925.88      6763429.84
#Sta/Elev= 30
  4918.8 2178.54  4926.4 2178.94  4934.2 2177.94  4944.4 2174.39  4954.5 2169.34
  4964.7 2163.83  4973.9 2157.55  4979.0 2158.50  4982.0 2155.78  4985.1 2152.96
  4995.2 2147.17  4999.9 2145.22  5000.2 2144.72  5003.7 2144.72  5003.9 2145.22
  5007.4 2145.22  5013.1 2147.80  5018.7 2148.53  5028.3 2150.33  5050.9 2157.24
  5062.7 2161.66  5073.3 2161.76  5079.0 2162.90  5100.9 2165.44  5107.6 2167.01
  5117.2 2168.65  5119.9 2169.51  5130.3 2172.19  5144.9 2174.23  5155.0 2174.56
#Mann=5,-1,0
  4918.8    0.07       0  4982.0    0.16       0  4999.9    0.07       0
  5003.9    0.16       0  5119.9    0.07       0
Bank Sta=4999.9,5003.9
Exp/Cntr=0.3,0.1

Type RM Length L Ch R = 1,9918,52,52,52
BEGIN DESCRIPTION:
Elm 79 9918.19
END DESCRIPTION:
XS GIS Cut Line= 3
      1536759.21      6763264.90      1536806.09      6763384.71
      1536872.03      6763445.44
#Sta/Elev= 30
  4881.5 2174.32  4886.9 2176.24  4903.0 2172.12  4906.0 2171.23  4911.4 2171.62
  4917.0 2168.47  4935.9 2162.31  4941.2 2162.47  4949.3 2159.16  4960.0 2155.77
  4965.7 2152.66  4971.0 2150.97  4990.1 2147.55  4995.5 2143.63  5001.0 2142.63
  5001.2 2142.13  5004.7 2142.13  5005.0 2142.63  5012.8 2142.84  5018.9 2147.83
  5025.7 2150.96  5033.1 2155.09  5054.1 2163.11  5061.5 2165.09  5068.3 2167.69
  5075.6 2168.13  5082.8 2170.55  5089.8 2170.74  5096.6 2171.70  5099.8 2171.56
#Mann=5,-1,0
  4881.5    0.07       0  4903.0    0.16       0  5001.0    0.07       0
  5005.0    0.16       0  5082.8    0.07       0
Bank Sta=5001,5005
Exp/Cntr=0.3,0.1

Type RM Length L Ch R = 1,9866,70,70,70
BEGIN DESCRIPTION:
Elm 79 9865.89
END DESCRIPTION:
XS GIS Cut Line= 3
      1536689.79      6763303.14      1536755.74      6763391.65
      1536814.75      6763499.25
#Sta/Elev= 30
  4888.1 2170.38  4894.4 2168.00  4917.4 2162.18  4938.2 2159.51  4944.5 2159.38
  4952.8 2157.28  4959.1 2154.93  4973.7 2148.27  4988.3 2146.12  4993.7 2147.28
  5003.7 2147.34  5009.4 2146.69  5017.1 2142.17  5023.5 2140.49  5023.7 2139.99
  5027.2 2139.99  5027.5 2140.49  5039.9 2148.62  5047.3 2154.15  5053.0 2156.90
  5062.7 2162.86  5069.1 2167.39  5074.8 2169.36  5085.2 2171.76  5090.9 2171.63
  5093.3 2172.11  5097.0 2172.85  5107.0 2173.02  5112.7 2172.76  5121.2 2173.10
#Mann=4,-1,0
  4888.1    0.16       0  5023.5    0.07       0  5027.5    0.16       0
  5093.3    0.07       0
Bank Sta=5023.5,5027.5
Exp/Cntr=0.3,0.1

Type RM Length L Ch R = 1,9796,65,65,65
BEGIN DESCRIPTION:
Elm 79 9795.63
END DESCRIPTION:
XS GIS Cut Line= 3
      1536630.72      6763346.48      1536701.92      6763436.79
      1536769.82      6763513.17
#Sta/Elev= 30
  4881.7 2175.90  4885.9 2175.90  4893.3 2172.54  4899.7 2171.16  4907.8 2165.98
  4914.2 2164.52  4921.8 2160.28  4928.6 2157.09  4935.0 2157.21  4943.0 2156.54
  4957.5 2156.13  4971.9 2150.22  4978.3 2142.20  4990.7 2137.92  4991.0 2137.42
  4994.5 2137.42  4994.7 2137.92  4995.2 2142.17  5000.9 2142.17  5006.9 2145.75
  5013.6 2150.21  5021.2 2153.07  5027.8 2156.20  5042.1 2159.94  5049.6 2163.36
  5056.3 2165.44  5063.8 2168.71  5078.0 2171.01  5085.6 2171.82  5098.9 2173.10
#Mann=4,-1,0
  4881.7    0.16       0  4990.7    0.07       0  4994.7    0.16       0
  5085.6    0.07       0
Bank Sta=4990.7,4994.7
Exp/Cntr=0.3,0.1

Type RM Length L Ch R = 1,9731,104,104,104
BEGIN DESCRIPTION:
Elm 79 9730.57
END DESCRIPTION:
XS GIS Cut Line= 3
      1536566.54      6763374.32      1536658.52      6763485.40
      1536736.67      6763547.92
#Sta/Elev= 30
  4860.2 2173.00  4868.5 2173.44  4876.4 2170.25  4882.9 2169.04  4890.7 2164.74
  4897.2 2163.20  4903.9 2159.12  4911.5 2155.92  4940.2 2153.83  4946.7 2154.92
  4954.5 2152.06  4961.0 2152.86  4968.8 2150.56  4975.4 2147.08  4981.9 2149.06
  4989.7 2143.83  4996.2 2143.18  5002.9 2138.44  5009.5 2137.22  5009.7 2136.72
  5013.5 2137.22  5025.5 2142.12  5038.7 2150.68  5046.7 2153.20  5061.1 2161.11
  5075.5 2165.97  5081.0 2166.18  5096.3 2170.17  5100.5 2168.88  5104.5 2168.88
#Mann=4,-1,0
  4860.2    0.16       0  5009.5    0.07       0  5013.5    0.16       0
  5081.0    0.07       0
Bank Sta=5009.5,5013.5
Exp/Cntr=0.3,0.1

Type RM Length L Ch R = 1,9627,61,61,61
BEGIN DESCRIPTION:
Elm 79 9626.89
END DESCRIPTION:
XS GIS Cut Line= 3
      1536510.96      6763402.09      1536563.04      6763513.18
      1536706.93      6763553.05
#Sta/Elev= 30
  4899.6 2169.04  4906.1 2166.37  4921.8 2162.52  4928.2 2158.14  4939.1 2154.42
  4944.6 2153.13  4950.3 2149.30  4961.3 2146.18  4967.4 2142.42  4973.0 2140.45
  4983.4 2135.59  4988.3 2135.19  4988.5 2134.69  4992.0 2134.69  4992.3 2135.19
  5005.5 2143.88  5013.5 2148.36  5018.6 2148.37  5022.2 2152.33  5032.2 2152.56
  5059.9 2152.82  5065.8 2154.48  5086.6 2158.32  5094.1 2158.38  5099.3 2157.58
  5128.1 2158.14  5148.8 2159.50  5159.0 2160.95  5167.9 2162.90  5171.6 2161.93
#Mann=6,-1,0
  4899.6    0.16       0  4988.3    0.07       0  4992.3    0.16       0
  5013.5    0.07       0  5032.2    0.16       0  5159.0    0.07       0
Bank Sta=4988.3,4992.3
Exp/Cntr=0.3,0.1

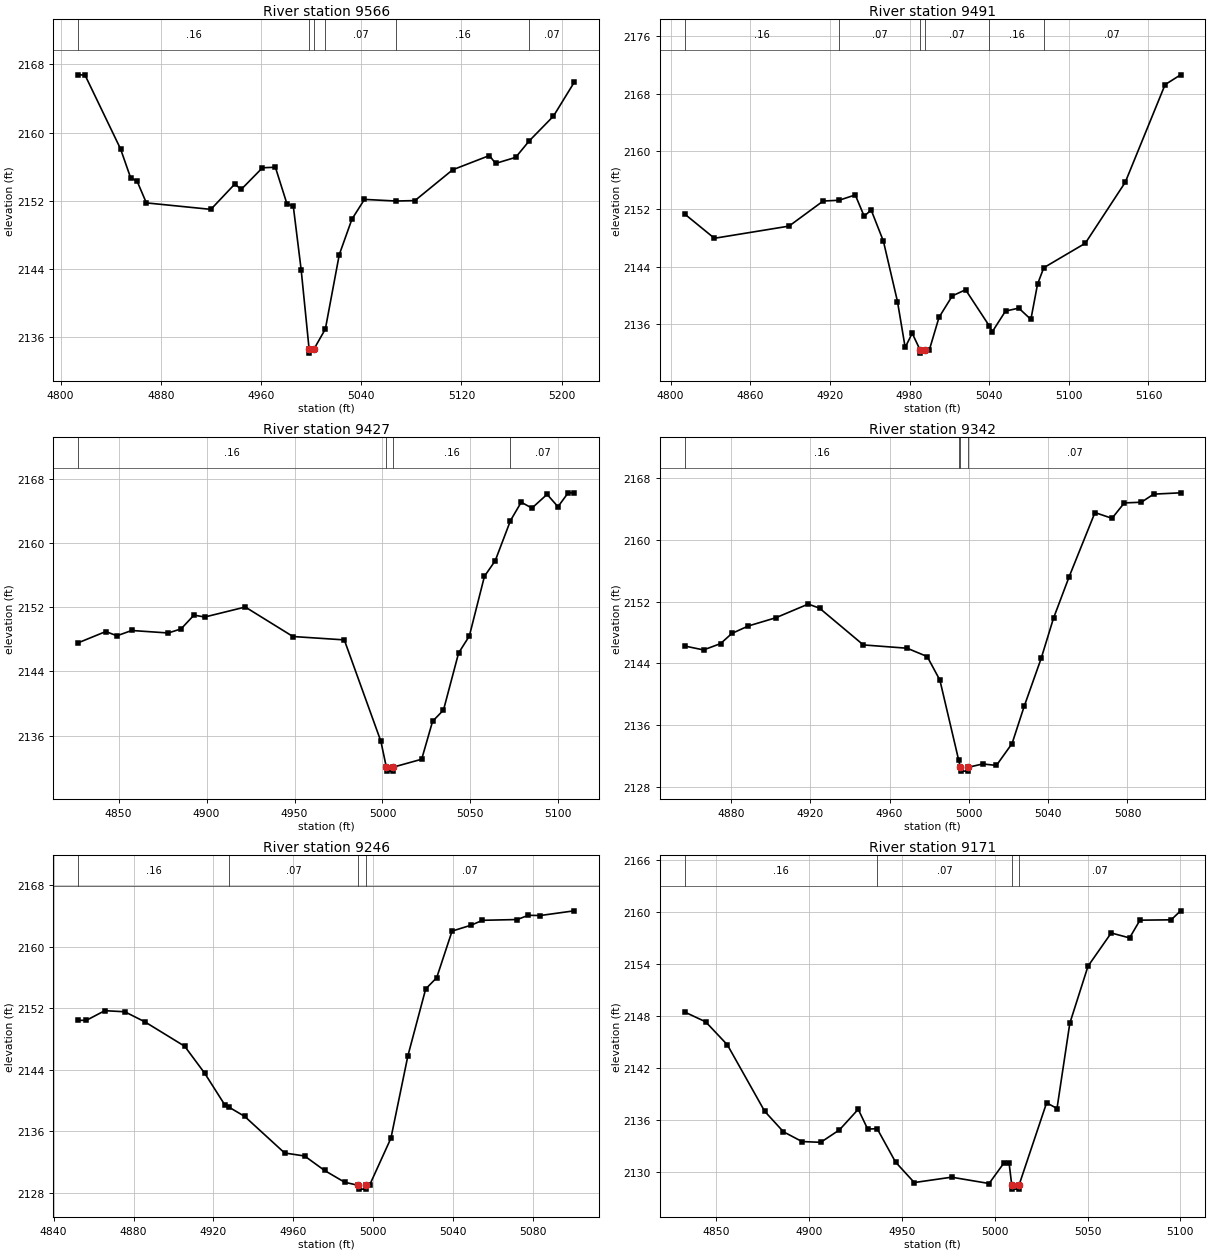
Type RM Length L Ch R = 1,9566,75,75,75
BEGIN DESCRIPTION:
Elm 79 9565.9
END DESCRIPTION:
XS GIS Cut Line= 3
      1536332.17      6763492.35      1536516.16      6763537.48
      1536721.39      6763559.90
#Sta/Elev= 30
  4814.1 2166.77  4819.5 2166.75  4847.9 2158.08  4855.9 2154.71  4861.1 2154.30
  4868.5 2151.75  4920.0 2150.99  4939.1 2153.96  4944.2 2153.33  4961.2 2155.87
  4971.5 2155.93  4980.7 2151.65  4985.8 2151.36  4992.1 2143.88  4998.4 2134.63
  4998.6 2134.13  5002.4 2134.63  5011.4 2136.96  5022.5 2145.68  5032.6 2149.84
  5042.6 2152.16  5067.6 2151.97  5082.9 2152.02  5113.0 2155.63  5142.3 2157.30
  5147.3 2156.38  5163.3 2157.09  5174.2 2159.03  5193.5 2161.93  5210.0 2165.88
#Mann=6,-1,0
  4814.1    0.16       0  4998.4    0.07       0  5002.4    0.16       0
  5011.4    0.07       0  5067.6    0.16       0  5174.2    0.07       0
Bank Sta=4998.4,5002.4
Exp/Cntr=0.3,0.1

Type RM Length L Ch R = 1,9491,64,64,64
BEGIN DESCRIPTION:
Elm 79 9490.99
END DESCRIPTION:
XS GIS Cut Line= 3
      1536373.84      6763537.50      1536545.67      6763598.25
      1536736.63      6763586.10
#Sta/Elev= 30
  4810.6 2151.31  4833.0 2147.94  4889.2 2149.63  4914.9 2153.11  4926.9 2153.22
  4939.1 2153.96  4945.8 2151.01  4951.1 2151.86  4960.3 2147.54  4970.9 2139.16
  4976.7 2132.78  4982.0 2134.75  4987.8 2132.49  4988.1 2131.99  4991.8 2132.49
  4995.0 2132.49  5002.2 2136.96  5012.2 2139.94  5022.2 2140.79  5040.0 2135.79
  5042.3 2134.95  5052.3 2137.83  5062.3 2138.24  5071.4 2136.67  5076.4 2141.55
  5081.1 2143.85  5112.4 2147.25  5142.5 2155.72  5172.5 2169.28  5184.2 2170.64
#Mann=6,-1,0
  4810.6    0.16       0  4926.9    0.07       0  4987.8    0.07       0
  4991.8    0.07       0  5040.0    0.16       0  5081.1    0.07       0
Bank Sta=4987.8,4991.8
Exp/Cntr=0.3,0.1

Type RM Length L Ch R = 1,9427,85,85,85
BEGIN DESCRIPTION:
Elm 79 9426.97
END DESCRIPTION:
XS GIS Cut Line= 3
      1536398.07      6763553.08      1536540.47      6763659.01
      1536625.52      6763719.77
#Sta/Elev= 30
  4827.0 2147.56  4842.7 2148.96  4849.0 2148.43  4857.4 2149.09  4878.2 2148.78
  4885.5 2149.29  4892.8 2151.00  4899.0 2150.77  4922.0 2152.01  4949.1 2148.34
  4978.3 2147.92  4999.1 2135.30  5002.2 2132.09  5002.4 2131.59  5005.9 2131.59
  5006.2 2132.09  5022.3 2133.07  5028.5 2137.79  5034.7 2139.19  5043.3 2146.29
  5049.4 2148.40  5058.0 2155.84  5064.1 2157.76  5072.8 2162.77  5078.9 2165.05
  5085.0 2164.32  5093.6 2166.03  5099.8 2164.49  5105.6 2166.22  5109.0 2166.22
#Mann=4,-1,0
  4827.0    0.16       0  5002.2    0.07       0  5006.2    0.16       0
  5072.8    0.07       0
Bank Sta=5002.2,5006.2
Exp/Cntr=0.3,0.1

Type RM Length L Ch R = 1,9342,96,96,96
BEGIN DESCRIPTION:
Elm 79 9341.59
END DESCRIPTION:
XS GIS Cut Line= 3
      1536410.25      6763589.55      1536476.23      6763716.30
      1536538.05      6763803.88
#Sta/Elev= 30
  4856.7 2146.25  4866.2 2145.74  4874.8 2146.56  4880.5 2147.88  4888.8 2148.85
  4902.6 2149.91  4919.0 2151.69  4924.7 2151.16  4946.8 2146.39  4968.9 2145.96
  4979.0 2144.88  4985.4 2141.82  4994.9 2131.41  4995.7 2130.51  4996.0 2130.01
  4999.5 2130.01  4999.7 2130.51  5007.0 2130.94  5013.9 2130.75  5021.8 2133.59
  5027.9 2138.41  5036.5 2144.66  5042.7 2149.86  5050.6 2155.25  5063.6 2163.57
  5072.2 2162.82  5078.4 2164.82  5087.0 2164.91  5093.2 2165.96  5106.8 2166.13
#Mann=4,-1,0
  4856.7    0.16       0  4994.9    0.07       0  4995.7    0.07       0
  4999.7    0.07       0
Bank Sta=4995.7,4999.7
Exp/Cntr=0.3,0.1

Type RM Length L Ch R = 1,9246,75,75,75
BEGIN DESCRIPTION:
Elm 79 9246.27
END DESCRIPTION:
XS GIS Cut Line= 3
      1536405.05      6763634.75      1536406.79      6763780.54
      1536449.80      6763873.46
#Sta/Elev= 30
  4852.3 2150.42  4856.4 2150.42  4865.6 2151.67  4875.6 2151.53  4885.6 2150.23
  4905.6 2147.05  4915.6 2143.55  4925.6 2139.47  4927.8 2139.14  4935.6 2137.95
  4955.6 2133.20  4965.6 2132.81  4975.6 2130.93  4985.6 2129.41  4992.3 2129.01
  4992.6 2128.51  4996.1 2128.51  4996.3 2129.01  4998.1 2129.01  5008.8 2135.12
  5017.3 2145.82  5026.2 2154.49  5031.7 2155.95  5039.4 2162.00  5049.1 2162.78
  5054.6 2163.40  5072.0 2163.50  5077.6 2164.05  5083.5 2164.02  5100.5 2164.63
#Mann=4,-1,0
  4852.3    0.16       0  4927.8    0.07       0  4992.3    0.07       0
  4996.3    0.07       0
Bank Sta=4992.3,4996.3
Exp/Cntr=0.3,0.1

Type RM Length L Ch R = 1,9171,110,110,110
BEGIN DESCRIPTION:
Elm 79 9170.76
END DESCRIPTION:
XS GIS Cut Line= 3
      1536318.25      6763605.21      1536339.08      6763778.80
      1536380.38      6763861.41
#Sta/Elev= 30
  4832.9 2148.44  4844.2 2147.31  4855.9 2144.65  4876.0 2136.97  4886.1 2134.60
  4896.1 2133.47  4906.2 2133.38  4916.3 2134.82  4926.4 2137.20  4931.5 2134.91
  4936.6 2134.96  4946.5 2131.10  4956.6 2128.73  4976.7 2129.35  4996.9 2128.62
  5004.8 2130.96  5007.7 2130.96  5009.1 2128.47  5009.4 2127.97  5012.9 2127.97
  5013.1 2128.47  5027.9 2137.95  5033.5 2137.29  5040.4 2147.14  5050.2 2153.74
  5062.7 2157.58  5072.6 2157.01  5078.2 2159.06  5095.0 2159.10  5100.1 2160.14
#Mann=4,-1,0
  4832.9    0.16       0  4936.6    0.07       0  5009.1    0.07       0
  5013.1    0.07       0
Bank Sta=5009.1,5013.1
Exp/Cntr=0.3,0.1

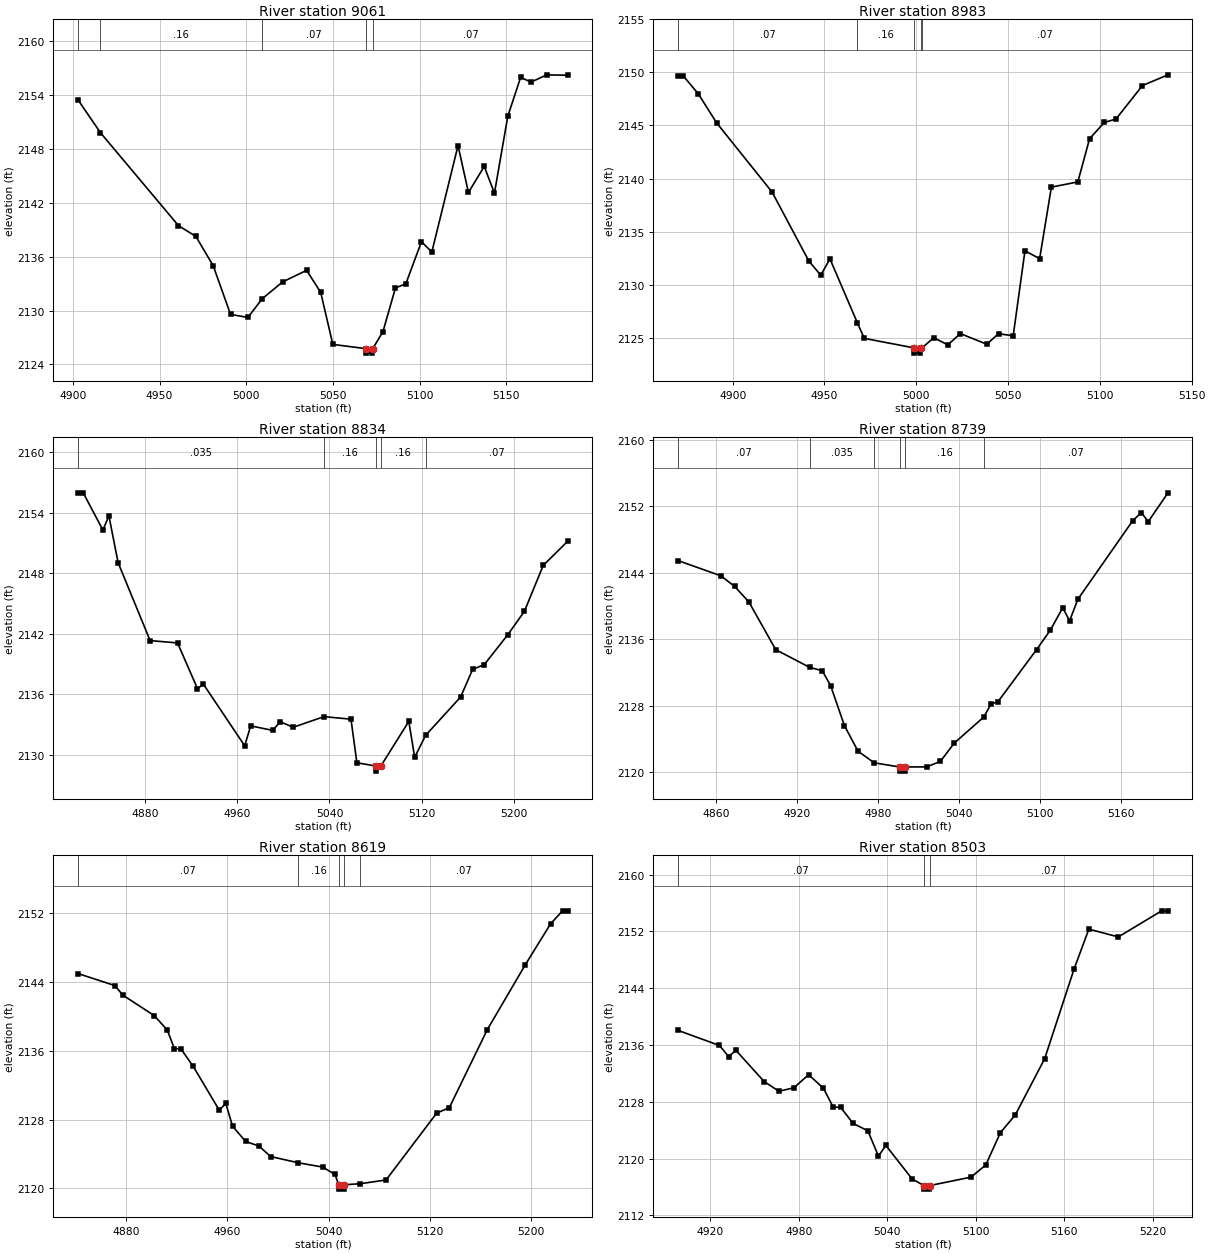
Type RM Length L Ch R = 1,9061,78,78,78
BEGIN DESCRIPTION:
Elm 79 9061.33
END DESCRIPTION:
XS GIS Cut Line= 3
      1536255.74      6763600.00      1536259.22      6763728.46
      1536344.29      6763856.94
#Sta/Elev= 30
  4902.9 2153.45  4915.9 2149.78  4960.9 2139.44  4970.9 2138.25  4980.9 2134.99
  4990.9 2129.57  5000.9 2129.23  5009.2 2131.31  5020.9 2133.18  5034.8 2134.47
  5042.9 2132.02  5049.9 2126.23  5068.9 2125.76  5069.2 2125.26  5072.7 2125.26
  5072.9 2125.76  5078.8 2127.65  5086.0 2132.51  5092.0 2132.98  5101.0 2137.65
  5107.0 2136.52  5122.1 2148.35  5128.1 2143.13  5137.2 2146.03  5143.1 2143.06
  5150.8 2151.62  5158.2 2155.94  5164.2 2155.41  5173.3 2156.22  5185.5 2156.17
#Mann=5,-1,0
  4902.9    0.07       0  4915.9    0.16       0  5009.2    0.07       0
  5068.9    0.07       0  5072.9    0.07       0
Bank Sta=5068.9,5072.9
Exp/Cntr=0.3,0.1

Type RM Length L Ch R = 1,8983,149,149,149
BEGIN DESCRIPTION:
Elm 79 8983.32
END DESCRIPTION:
XS GIS Cut Line= 3
      1536182.83      6763606.94      1536194.98      6763740.61
      1536298.59      6763823.50
#Sta/Elev= 30
  4870.2 2149.65  4873.2 2149.65  4881.3 2147.98  4891.3 2145.24  4921.5 2138.72
  4941.5 2132.23  4948.0 2130.89  4953.0 2132.43  4968.0 2126.38  4971.7 2124.94
  4998.6 2124.05  4998.8 2123.55  5002.3 2123.55  5002.6 2124.05  5003.2 2124.05
  5009.5 2125.00  5017.2 2124.33  5024.0 2125.39  5038.4 2124.39  5044.8 2125.38
  5052.8 2125.18  5059.2 2133.19  5067.2 2132.45  5073.6 2139.19  5088.0 2139.68
  5094.4 2143.75  5102.4 2145.28  5108.8 2145.61  5123.2 2148.76  5137.1 2149.77
#Mann=5,-1,0
  4870.2    0.07       0  4968.0    0.16       0  4998.6    0.07       0
  5002.6    0.16       0  5003.2    0.07       0
Bank Sta=4998.6,5002.6
Exp/Cntr=0.3,0.1

Type RM Length L Ch R = 1,8834,95,95,95
BEGIN DESCRIPTION:
Elm 79 8834.19
END DESCRIPTION:
XS GIS Cut Line= 3
      1535891.15      6763737.14      1536063.04      6763780.54
      1536306.10      6763830.89
#Sta/Elev= 30
  4821.6 2155.99  4826.2 2155.99  4843.3 2152.30  4848.5 2153.71  4856.5 2149.06
  4884.3 2141.34  4908.1 2141.11  4925.4 2136.58  4930.6 2137.01  4966.4 2130.91
  4971.6 2132.89  4990.6 2132.44  4997.3 2133.29  5008.5 2132.75  5035.3 2133.80
  5058.7 2133.55  5063.8 2129.23  5080.6 2128.90  5080.8 2128.40  5084.6 2128.90
  5108.9 2133.33  5114.0 2129.77  5123.5 2131.95  5153.9 2135.75  5164.3 2138.48
  5174.5 2138.97  5194.9 2141.93  5209.2 2144.23  5225.6 2148.79  5247.1 2151.22
#Mann=5,-1,0
  4821.6   0.035       0  5035.3    0.16       0  5080.6   0.035       0
  5084.6    0.16       0  5123.5    0.07       0
Bank Sta=5080.6,5084.6
Exp/Cntr=0.3,0.1

Type RM Length L Ch R = 1,8739,120,120,120
BEGIN DESCRIPTION:
Elm 79 8739.43
END DESCRIPTION:
XS GIS Cut Line= 3
      1535953.65      6763881.24      1536122.06      6763851.72
      1536310.64      6763886.32
#Sta/Elev= 30
  4831.8 2145.47  4863.6 2143.63  4873.8 2142.35  4884.3 2140.49  4904.2 2134.74
  4929.3 2132.61  4938.6 2132.21  4944.8 2130.42  4955.0 2125.61  4965.1 2122.52
  4977.1 2121.12  4996.0 2120.62  4996.3 2120.12  4999.8 2120.12  5000.0 2120.62
  5015.9 2120.63  5026.1 2121.30  5036.3 2123.49  5058.3 2126.65  5063.5 2128.21
  5068.6 2128.46  5097.3 2134.76  5107.4 2137.08  5116.6 2139.79  5121.7 2138.21
  5127.8 2140.81  5168.4 2150.26  5174.8 2151.25  5179.9 2150.15  5194.5 2153.62
#Mann=6,-1,0
  4831.8    0.07       0  4929.3   0.035       0  4977.1    0.16       0
  4996.0    0.07       0  5000.0    0.16       0  5058.3    0.07       0
Bank Sta=4996,5000
Exp/Cntr=0.3,0.1

Type RM Length L Ch R = 1,8619,116,116,116
BEGIN DESCRIPTION:
Elm 79 8618.95
END DESCRIPTION:
XS GIS Cut Line= 3
      1535946.76      6763903.82      1536101.23      6763943.73
      1536328.66      6763940.26
#Sta/Elev= 30
  4842.0 2144.95  4871.2 2143.55  4877.5 2142.44  4902.2 2140.07  4912.5 2138.41
  4918.2 2136.22  4923.3 2136.21  4933.1 2134.16  4953.6 2129.09  4958.8 2129.87
  4964.1 2127.23  4974.5 2125.45  4984.8 2124.93  4994.3 2123.70  5016.0 2122.98
  5035.3 2122.48  5045.0 2121.62  5048.0 2120.42  5048.3 2119.92  5051.8 2119.92
  5052.0 2120.42  5065.0 2120.55  5085.3 2120.98  5125.3 2128.74  5135.3 2129.38
  5165.3 2138.44  5195.3 2145.97  5215.3 2150.73  5224.7 2152.23  5229.0 2152.23
#Mann=5,-1,0
  4842.0    0.07       0  5016.0    0.16       0  5048.0    0.07       0
  5052.0    0.16       0  5065.0    0.07       0
Bank Sta=5048,5052
Exp/Cntr=0.3,0.1

Type RM Length L Ch R = 1,8503,80,80,80
BEGIN DESCRIPTION:
Elm 79 8502.89
END DESCRIPTION:
XS GIS Cut Line= 3
      1535997.02      6764018.38      1536102.97      6764032.28
      1536328.65      6764037.48
#Sta/Elev= 30
  4897.9 2138.06  4926.1 2135.93  4932.3 2134.37  4937.3 2135.24  4956.4 2130.85
  4966.5 2129.48  4976.6 2129.97  4986.6 2131.81  4996.7 2129.90  5003.3 2127.23
  5008.3 2127.23  5016.8 2124.94  5026.8 2123.91  5034.0 2120.34  5039.0 2121.85
  5056.8 2117.14  5064.8 2116.19  5065.1 2115.69  5068.6 2115.69  5068.8 2116.19
  5096.8 2117.38  5106.8 2119.08  5116.8 2123.66  5126.8 2126.12  5146.8 2134.06
  5166.8 2146.72  5176.8 2152.32  5196.8 2151.22  5226.2 2154.90  5230.5 2154.90
#Mann=3,-1,0
  4897.9    0.07       0  5064.8    0.07       0  5068.8    0.07       0
Bank Sta=5064.8,5068.8
Exp/Cntr=0.3,0.1