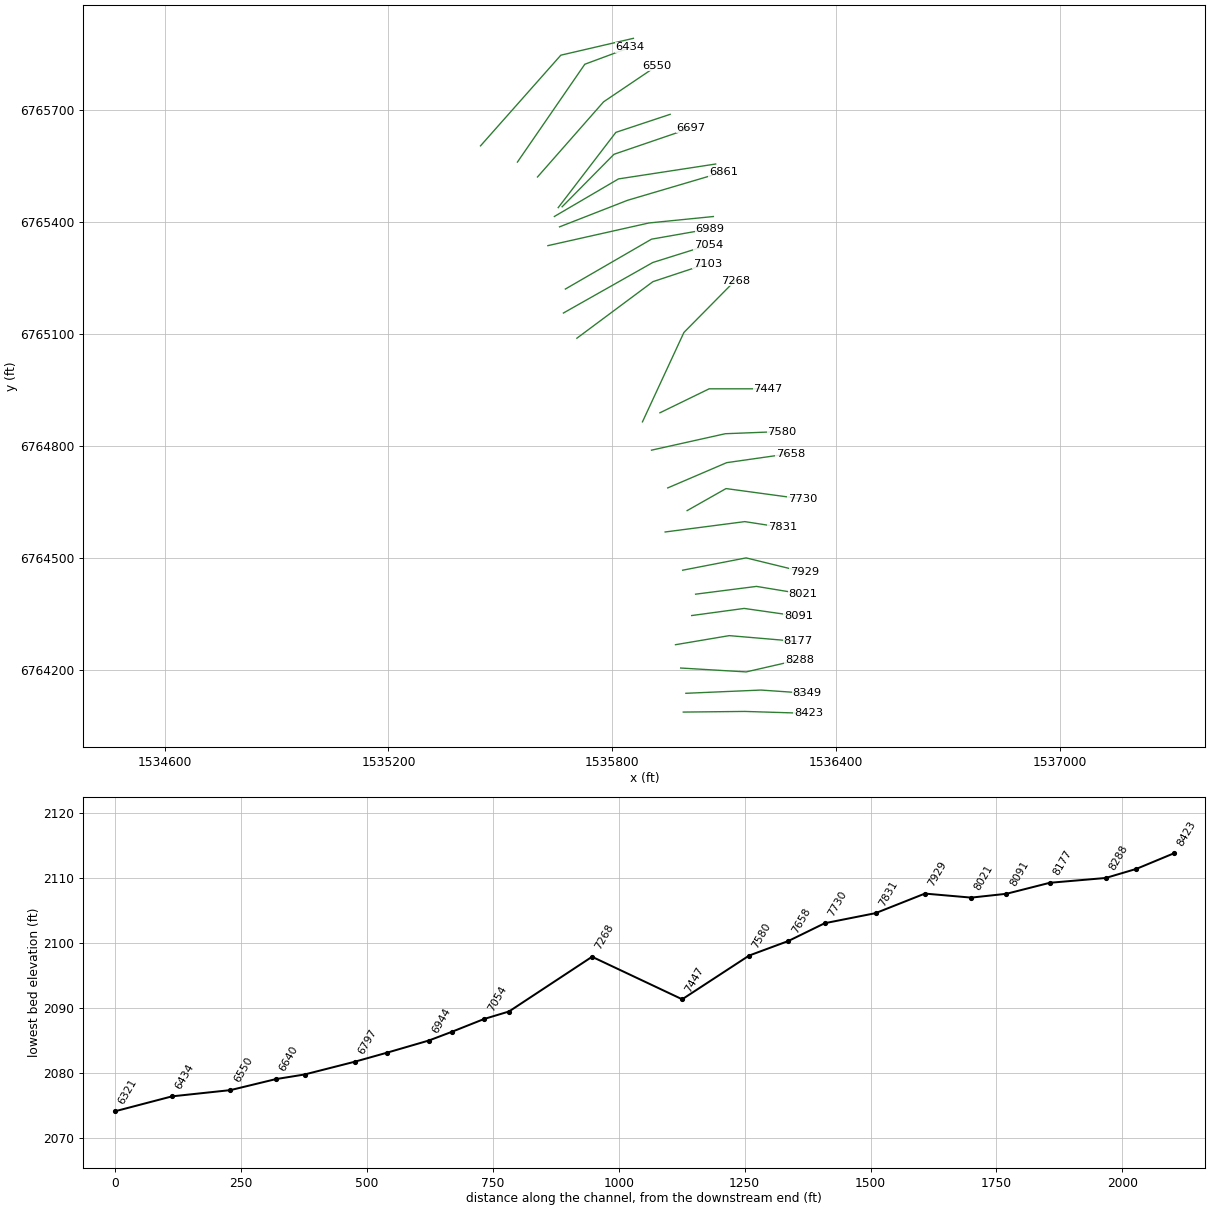
HEC-RAS study Elm 79.prj: Elm 79 Base Level Engineering

--- Elm 79.g01 (geometry) --- (continued)

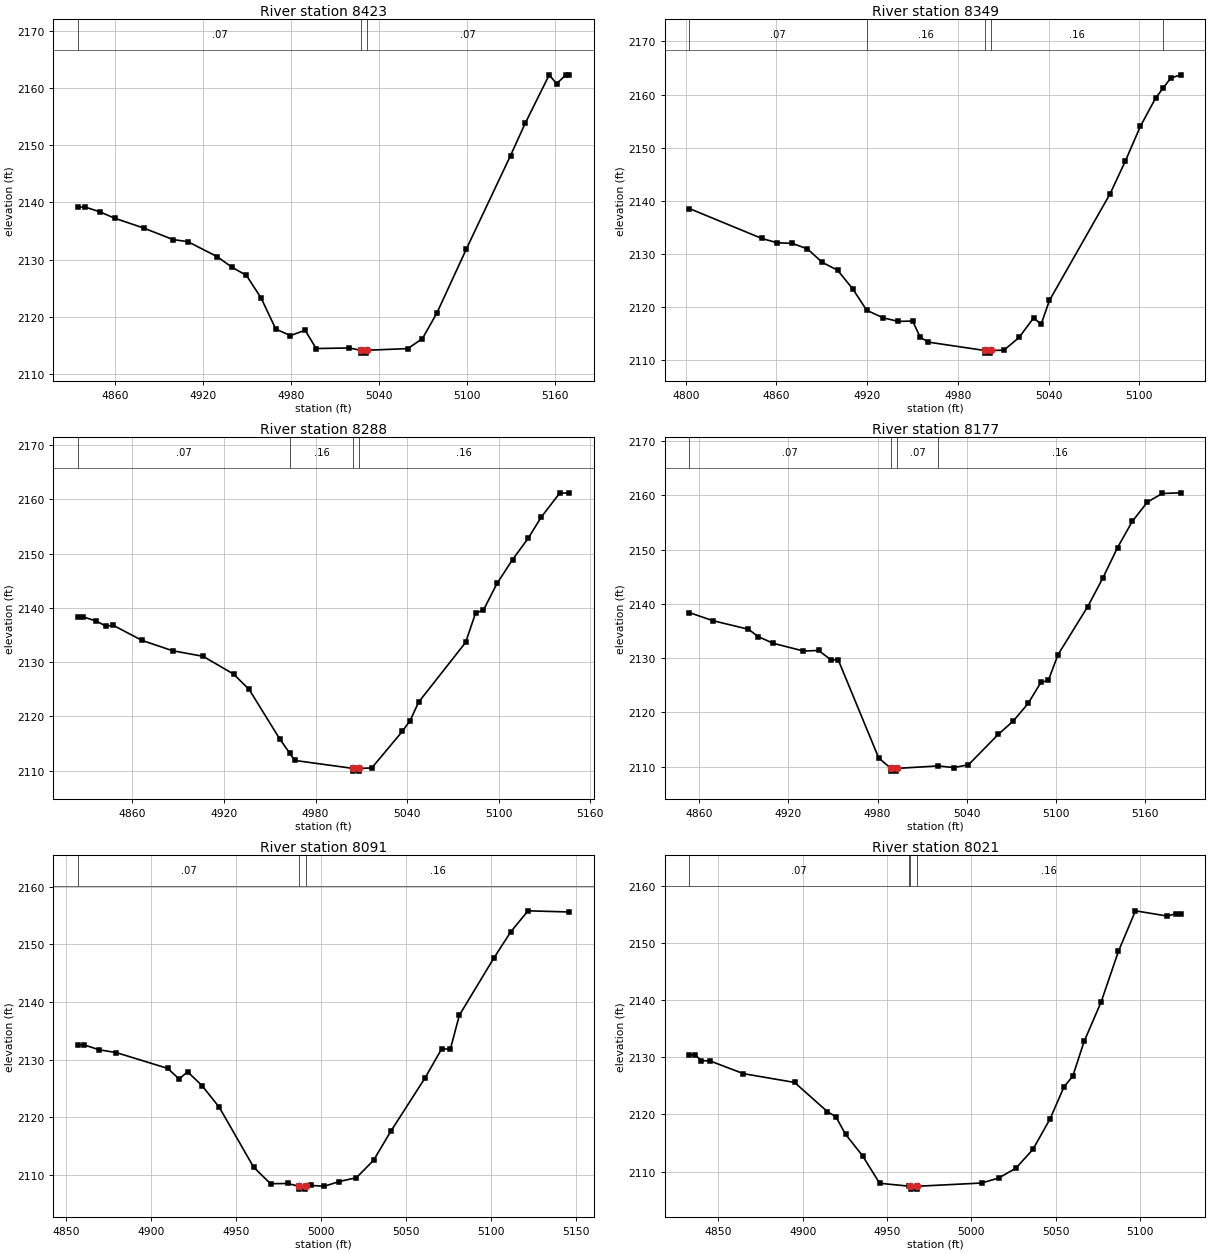
Type RM Length L Ch R = 1,8423,74,74,74
BEGIN DESCRIPTION:
Elm 79 8422.83
END DESCRIPTION:
XS GIS Cut Line= 3
      1535990.12      6764086.10      1536155.05      6764087.83
      1536325.23      6764082.62
#Sta/Elev= 30
  4834.8 2139.20  4839.7 2139.20  4849.7 2138.37  4859.7 2137.27  4879.7 2135.53
  4899.7 2133.52  4909.7 2133.17  4929.7 2130.55  4939.7 2128.72  4949.7 2127.27
  4959.7 2123.32  4969.7 2117.90  4979.7 2116.77  4989.7 2117.71  4997.2 2114.51
  5019.7 2114.61  5027.7 2114.21  5028.0 2113.71  5031.5 2113.71  5031.7 2114.21
  5059.7 2114.50  5069.7 2116.24  5079.7 2120.78  5099.7 2131.90  5129.8 2148.19
  5139.8 2153.82  5156.2 2162.28  5161.2 2160.72  5167.4 2162.23  5170.0 2162.23
#Mann=3,-1,0
  4834.8    0.07       0  5027.7    0.07       0  5031.7    0.07       0
Bank Sta=5027.7,5031.7
Exp/Cntr=0.3,0.1

Type RM Length L Ch R = 1,8349,61,61,61
BEGIN DESCRIPTION:
Elm 79 8349.12
END DESCRIPTION:
XS GIS Cut Line= 3
      1535997.08      6764136.44      1536198.45      6764145.12
      1536321.69      6764136.56
#Sta/Elev= 30
  4802.4 2138.55  4850.4 2132.91  4860.4 2132.11  4870.4 2131.99  4880.4 2130.97
  4890.4 2128.40  4900.4 2126.95  4910.4 2123.46  4919.7 2119.40  4930.4 2117.99
  4940.4 2117.31  4950.1 2117.36  4955.1 2114.33  4960.5 2113.40  4997.7 2111.83
  4998.0 2111.33  5001.5 2111.33  5001.7 2111.83  5010.5 2111.88  5020.5 2114.28
  5030.1 2117.96  5035.1 2116.77  5040.6 2121.26  5080.7 2141.32  5090.7 2147.43
  5100.7 2154.00  5110.8 2159.34  5115.9 2161.26  5120.8 2163.11  5127.5 2163.72
#Mann=5,-1,0
  4802.4    0.07       0  4919.7    0.16       0  4997.7    0.07       0
  5001.7    0.16       0  5115.9    0.07       0
Bank Sta=4997.7,5001.7
Exp/Cntr=0.3,0.1

Type RM Length L Ch R = 1,8288,111,111,111
BEGIN DESCRIPTION:
Elm 79 8287.85
END DESCRIPTION:
XS GIS Cut Line= 3
      1535983.14      6764204.15      1536158.52      6764193.73
      1536301.34      6764226.43
#Sta/Elev= 30
  4824.3 2138.34  4827.8 2138.34  4836.2 2137.60  4842.5 2136.66  4847.5 2136.79
  4866.2 2134.03  4886.3 2132.12  4906.3 2131.09  4926.3 2127.81  4936.4 2125.02
  4956.4 2115.93  4963.2 2113.19  4966.4 2111.90  5004.6 2110.43  5004.9 2109.93
  5008.4 2109.93  5008.6 2110.43  5016.9 2110.52  5036.9 2117.25  5042.0 2119.24
  5047.7 2122.68  5078.4 2133.65  5084.9 2139.03  5090.1 2139.62  5099.0 2144.52
  5109.2 2148.92  5119.5 2152.87  5127.9 2156.71  5140.0 2161.14  5146.5 2161.22
#Mann=4,-1,0
  4824.3    0.07       0  4963.2    0.16       0  5004.6    0.07       0
  5008.6    0.16       0
Bank Sta=5004.6,5008.6
Exp/Cntr=0.3,0.1

Type RM Length L Ch R = 1,8177,86,86,86
BEGIN DESCRIPTION:
Elm 79 8176.79
END DESCRIPTION:
XS GIS Cut Line= 3
      1535969.24      6764266.64      1536113.38      6764290.96
      1536297.44      6764275.33
#Sta/Elev= 30
  4853.3 2138.41  4869.3 2136.91  4893.1 2135.34  4899.7 2133.98  4909.8 2132.75
  4930.1 2131.33  4940.3 2131.43  4948.5 2129.74  4953.6 2129.66  4980.8 2111.61
  4989.0 2109.69  4989.2 2109.19  4992.7 2109.19  4993.0 2109.69  5020.7 2110.15
  5031.2 2109.85  5041.2 2110.35  5061.3 2115.97  5071.4 2118.43  5081.4 2121.67
  5090.0 2125.56  5095.0 2125.90  5101.5 2130.66  5121.5 2139.51  5131.6 2144.73
  5141.6 2150.41  5151.6 2155.26  5161.7 2158.79  5171.7 2160.37  5184.2 2160.49
#Mann=4,-1,0
  4853.3    0.07       0  4989.0    0.07       0  4993.0    0.07       0
  5020.7    0.16       0
Bank Sta=4989,4993
Exp/Cntr=0.3,0.1

Type RM Length L Ch R = 1,8091,70,70,70
BEGIN DESCRIPTION:
Elm 79 8091.19
END DESCRIPTION:
XS GIS Cut Line= 3
      1536012.68      6764344.78      1536153.31      6764363.87
      1536299.11      6764343.05
#Sta/Elev= 30
  4856.8 2132.55  4860.5 2132.55  4869.2 2131.70  4879.3 2131.22  4909.6 2128.47
  4916.3 2126.63  4921.3 2127.88  4929.8 2125.47  4939.9 2121.73  4960.1 2111.33
  4970.1 2108.44  4980.2 2108.48  4986.8 2108.00  4987.0 2107.50  4990.5 2107.50
  4990.8 2108.00  4993.8 2108.14  5001.8 2108.00  5010.5 2108.82  5020.6 2109.48
  5030.7 2112.50  5040.8 2117.52  5061.0 2126.81  5070.8 2131.87  5075.9 2131.81
  5081.2 2137.71  5101.4 2147.59  5111.5 2152.21  5121.6 2155.84  5146.0 2155.64
#Mann=3,-1,0
  4856.8    0.07       0  4986.8    0.07       0  4990.8    0.16       0
Bank Sta=4986.8,4990.8
Exp/Cntr=0.3,0.1

Type RM Length L Ch R = 1,8021,92,92,92
BEGIN DESCRIPTION:
Elm 79 8021.34
END DESCRIPTION:
XS GIS Cut Line= 3
      1536023.14      6764402.07      1536186.30      6764422.90
      1536311.54      6764402.31
#Sta/Elev= 30
  4832.8 2130.48  4836.2 2130.48  4839.9 2129.44  4845.0 2129.40  4864.9 2127.16
  4895.2 2125.62  4914.7 2120.49  4919.7 2119.60  4925.4 2116.52  4935.5 2112.76
  4945.6 2107.94  4963.0 2107.43  4963.7 2107.41  4964.0 2106.91  4967.5 2106.91
  4967.7 2107.41  5006.1 2107.98  5016.2 2108.86  5026.4 2110.58  5036.5 2113.88
  5046.6 2119.19  5055.0 2124.89  5060.1 2126.70  5066.9 2132.84  5077.0 2139.78
  5087.2 2148.62  5097.3 2155.72  5116.2 2154.80  5121.3 2155.22  5124.2 2155.09
#Mann=4,-1,0
  4832.8    0.07       0  4963.0    0.16       0  4963.7    0.07       0
  4967.7    0.16       0
Bank Sta=4963.7,4967.7
Exp/Cntr=0.3,0.1

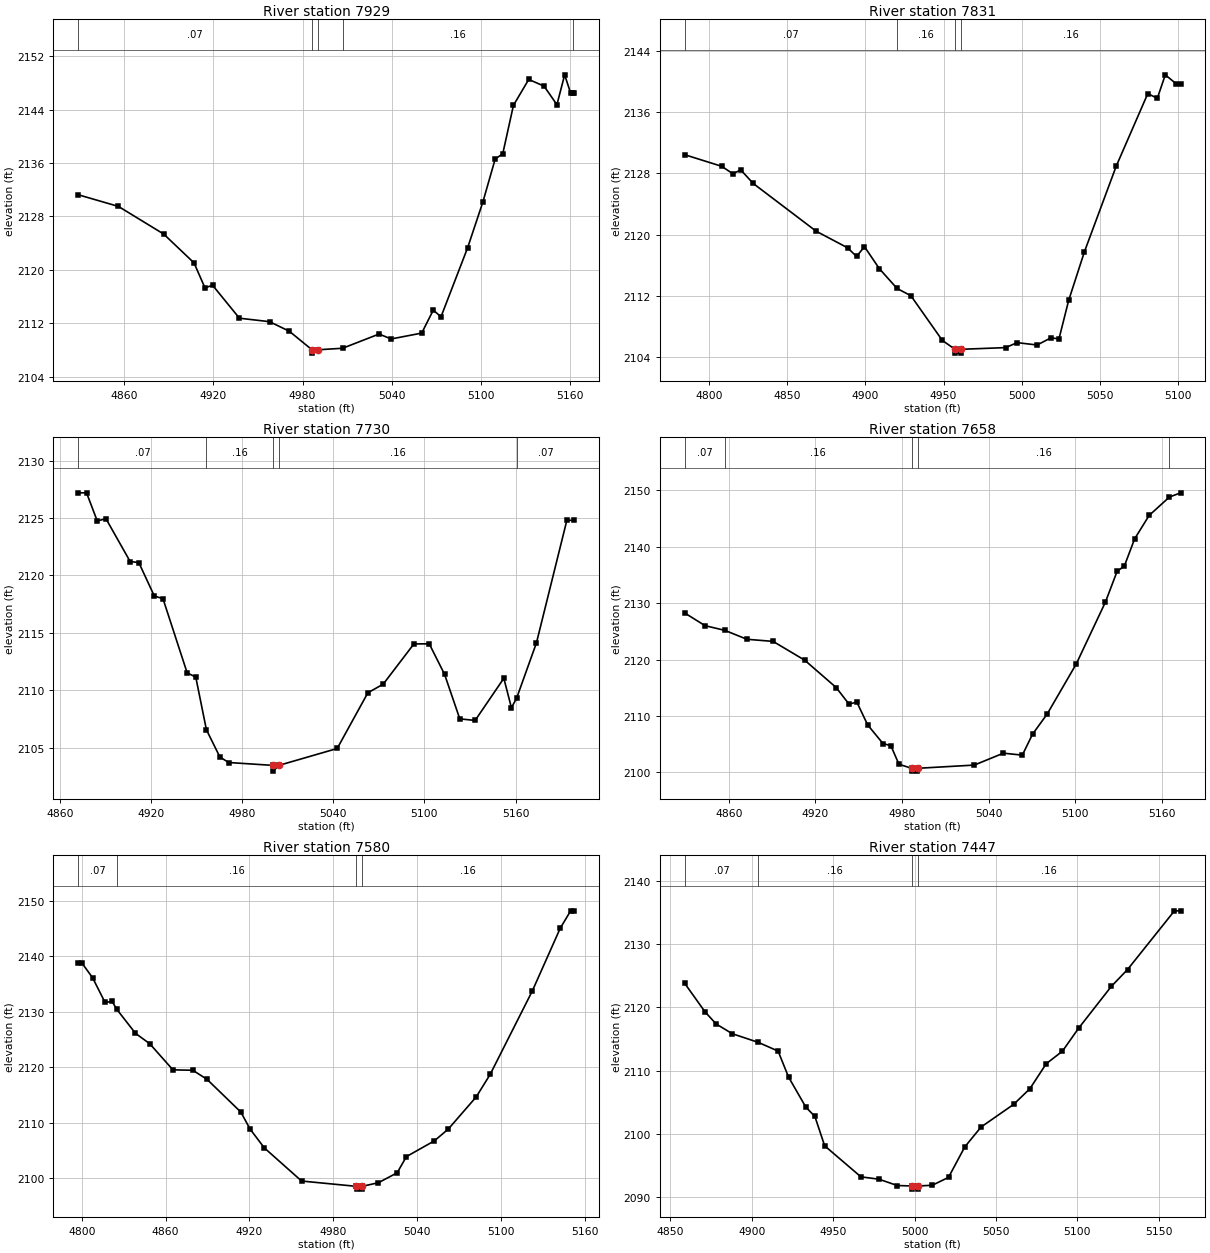
Type RM Length L Ch R = 1,7929,98,98,98
BEGIN DESCRIPTION:
Elm 79 7929.03
END DESCRIPTION:
XS GIS Cut Line= 3
      1535988.42      6764466.31      1536158.52      6764499.29
      1536314.75      6764461.10
#Sta/Elev= 30
  4828.9 2131.25  4856.0 2129.50  4886.5 2125.36  4906.9 2121.05  4914.3 2117.30
  4919.4 2117.70  4937.5 2112.76  4957.8 2112.24  4971.1 2110.81  4986.4 2108.03
  4986.6 2107.53  4990.4 2108.03  5007.0 2108.26  5031.6 2110.39  5039.7 2109.65
  5060.3 2110.53  5068.1 2113.97  5073.3 2112.97  5091.2 2123.29  5101.5 2130.16
  5109.8 2136.60  5114.9 2137.39  5122.1 2144.64  5132.4 2148.52  5142.7 2147.52
  5151.4 2144.74  5156.6 2149.21  5160.6 2146.49  5161.9 2146.49  5163.0 2146.49
#Mann=5,-1,0
  4828.9    0.07       0  4986.4    0.07       0  4990.4    0.07       0
  5007.0    0.16       0  5161.9    0.07       0
Bank Sta=4986.4,4990.4
Exp/Cntr=0.3,0.1

Type RM Length L Ch R = 1,7831,101,101,101
BEGIN DESCRIPTION:
Elm 79 7831.43
END DESCRIPTION:
XS GIS Cut Line= 3
      1535941.56      6764568.74      1536155.05      6764596.51
      1536255.75      6764580.89
#Sta/Elev= 30
  4784.4 2130.43  4808.0 2128.92  4815.2 2127.95  4820.3 2128.44  4828.2 2126.68
  4868.5 2120.44  4888.7 2118.26  4894.3 2117.14  4899.4 2118.42  4908.9 2115.55
  4920.2 2112.97  4929.1 2112.01  4949.2 2106.18  4957.3 2105.02  4957.6 2104.52
  4961.1 2104.52  4961.3 2105.02  4989.6 2105.24  4997.1 2105.89  5009.8 2105.58
  5018.7 2106.52  5023.8 2106.38  5030.0 2111.41  5040.1 2117.77  5060.4 2128.93
  5080.6 2138.41  5086.7 2137.79  5091.8 2140.86  5098.7 2139.70  5101.6 2139.70
#Mann=4,-1,0
  4784.4    0.07       0  4920.2    0.16       0  4957.3    0.07       0
  4961.3    0.16       0
Bank Sta=4957.3,4961.3
Exp/Cntr=0.3,0.1

Type RM Length L Ch R = 1,7730,72,72,72
BEGIN DESCRIPTION:
Elm 79 7729.89
END DESCRIPTION:
XS GIS Cut Line= 3
      1536000.51      6764626.01      1536104.70      6764685.05
      1536309.57      6764657.28
#Sta/Elev= 30
  4872.1 2127.19  4877.6 2127.19  4884.6 2124.75  4890.4 2124.93  4906.3 2121.21
  4912.0 2121.12  4922.2 2118.21  4927.9 2117.98  4943.8 2111.53  4949.5 2111.15
  4956.5 2106.57  4965.4 2104.19  4971.2 2103.72  5000.2 2103.47  5000.4 2102.97
  5004.2 2103.47  5042.6 2104.94  5062.8 2109.79  5072.9 2110.54  5093.1 2114.04
  5103.2 2114.05  5113.3 2111.39  5123.3 2107.52  5133.4 2107.38  5152.3 2111.05
  5157.3 2108.49  5160.7 2109.31  5173.8 2114.14  5193.8 2124.80  5198.6 2124.80
#Mann=5,-1,0
  4872.1    0.07       0  4956.5    0.16       0  5000.2    0.07       0
  5004.2    0.16       0  5160.7    0.07       0
Bank Sta=5000.2,5004.2
Exp/Cntr=0.3,0.1

Type RM Length L Ch R = 1,7658,78,78,78
BEGIN DESCRIPTION:
Elm 79 7658.4
END DESCRIPTION:
XS GIS Cut Line= 3
      1535948.49      6764686.81      1536106.44      6764754.50
      1536276.57      6764778.80
#Sta/Elev= 30
  4829.4 2128.25  4843.5 2126.00  4857.3 2125.16  4872.5 2123.59  4890.7 2123.21
  4912.6 2119.88  4934.4 2115.04  4943.3 2112.10  4948.7 2112.47  4956.2 2108.43
  4966.8 2105.13  4972.3 2104.74  4977.9 2101.45  4986.8 2100.74  4987.0 2100.24
  4990.5 2100.24  4990.8 2100.74  5030.1 2101.31  5050.3 2103.42  5063.4 2103.07
  5070.5 2106.79  5080.6 2110.34  5100.8 2119.23  5121.0 2130.18  5129.1 2135.63
  5134.1 2136.55  5141.2 2141.36  5151.3 2145.52  5165.3 2148.77  5173.1 2149.52
#Mann=5,-1,0
  4829.4    0.07       0  4857.3    0.16       0  4986.8    0.07       0
  4990.8    0.16       0  5165.3    0.07       0
Bank Sta=4986.8,4990.8
Exp/Cntr=0.3,0.1

Type RM Length L Ch R = 1,7580,133,133,133
BEGIN DESCRIPTION:
Elm 79 7580.306
END DESCRIPTION:
XS GIS Cut Line= 3
      1535904.98      6764788.00      1536102.73      6764832.06
      1536255.02      6764838.00
#Sta/Elev= 30
  4797.4 2138.79  4800.0 2138.79  4807.7 2136.12  4816.6 2131.67  4821.7 2131.85
  4824.9 2130.46  4838.4 2126.10  4848.6 2124.22  4865.2 2119.51  4879.4 2119.44
  4889.6 2117.80  4913.8 2111.90  4920.4 2108.84  4930.6 2105.44  4957.3 2099.46
  4996.6 2098.50  4996.9 2098.00  5000.4 2098.00  5000.6 2098.50  5012.3 2099.16
  5025.7 2100.94  5032.3 2103.86  5052.3 2106.70  5062.3 2108.83  5082.3 2114.63
  5092.3 2118.70  5122.4 2133.71  5142.4 2145.03  5149.9 2148.19  5152.4 2148.19
#Mann=4,-1,0
  4797.4    0.07       0  4824.9    0.16       0  4996.6    0.07       0
  5000.6    0.16       0
Bank Sta=4996.6,5000.6
Exp/Cntr=0.3,0.1

Type RM Length L Ch R = 1,7447,179,179,179
BEGIN DESCRIPTION:
Elm 79 7446.7
END DESCRIPTION:
XS GIS Cut Line= 3
      1535927.66      6764888.20      1536059.56      6764952.42
      1536217.55      6764952.42
#Sta/Elev= 30
  4858.8 2123.82  4871.2 2119.34  4878.1 2117.39  4888.1 2115.84  4903.9 2114.49
  4916.2 2113.10  4922.6 2109.00  4933.2 2104.25  4938.8 2102.76  4944.8 2098.12
  4967.1 2093.21  4978.2 2092.84  4989.4 2091.84  4998.2 2091.77  4998.4 2091.27
  5001.9 2091.27  5002.2 2091.77  5010.9 2091.88  5020.9 2093.13  5030.9 2097.95
  5040.9 2101.09  5060.9 2104.67  5070.9 2107.15  5080.9 2111.09  5090.9 2113.09
  5100.9 2116.74  5120.9 2123.32  5130.9 2126.00  5159.7 2135.28  5163.5 2135.28
#Mann=4,-1,0
  4858.8    0.07       0  4903.9    0.16       0  4998.2    0.07       0
  5002.2    0.16       0
Bank Sta=4998.2,5002.2
Exp/Cntr=0.3,0.1

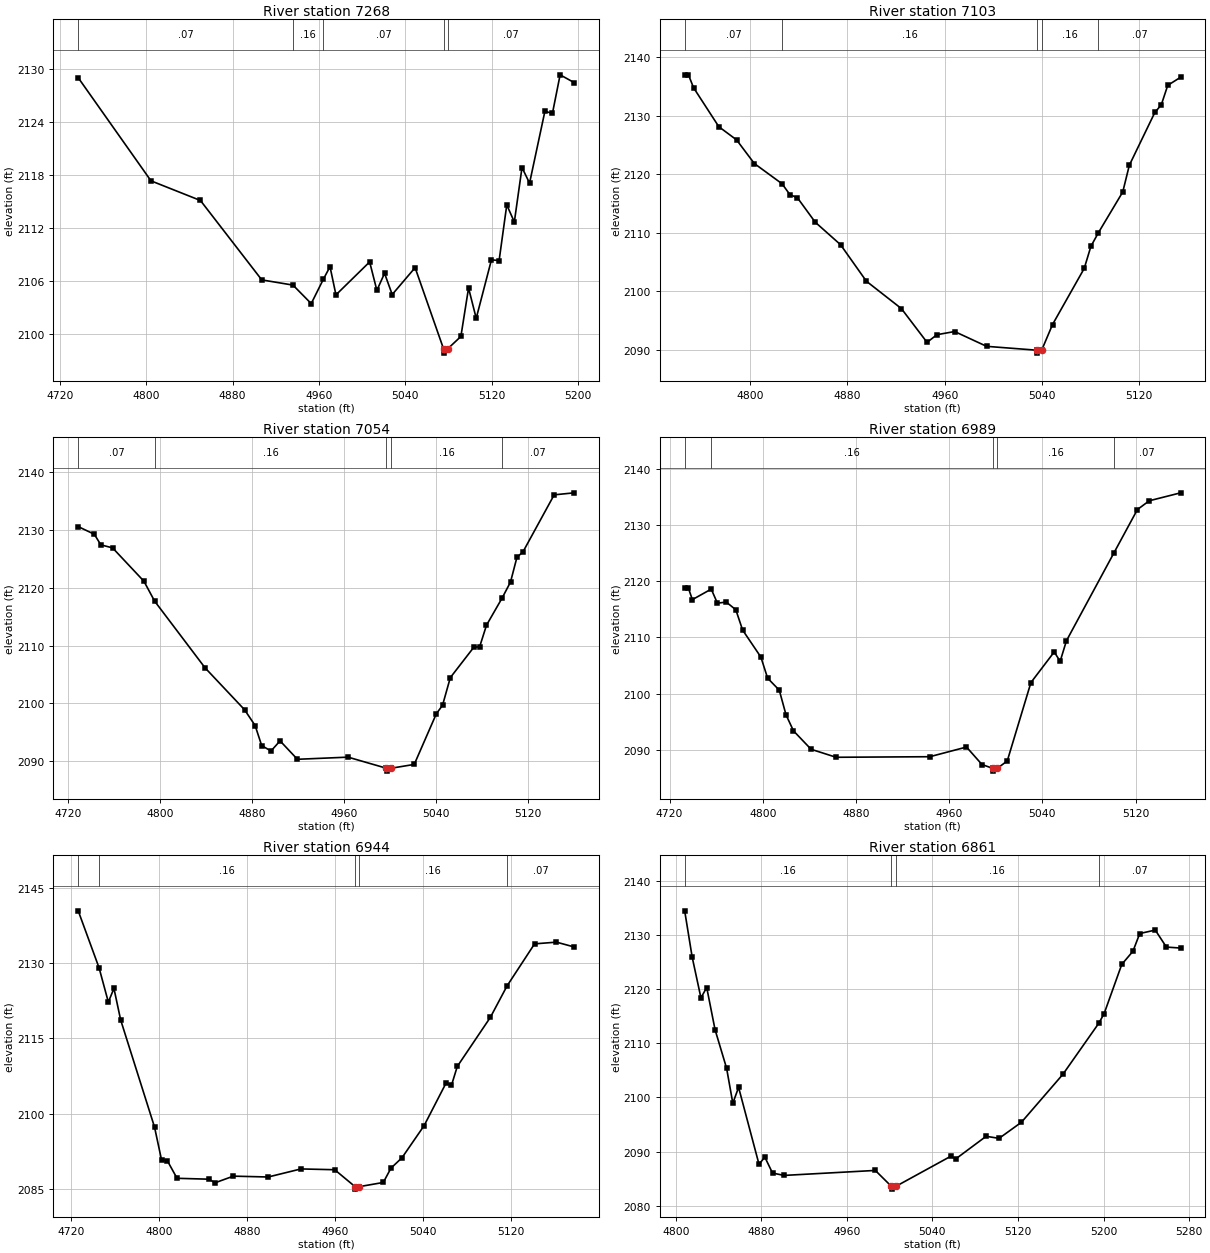
Type RM Length L Ch R = 1,7268,165,165,165
BEGIN DESCRIPTION:
Elm 79 7268.18
END DESCRIPTION:
XS GIS Cut Line= 3
      1535880.74      6764863.86      1535991.86      6765103.46
      1536129.00      6765242.34
#Sta/Elev= 30
  4737.1 2129.06  4804.5 2117.36  4850.3 2115.13  4907.1 2106.12  4936.0 2105.53
  4952.9 2103.43  4964.2 2106.21  4970.3 2107.62  4975.8 2104.42  5007.0 2108.16
  5013.7 2104.93  5020.8 2106.87  5027.9 2104.46  5049.1 2107.51  5075.4 2098.31
  5075.7 2097.81  5079.4 2098.31  5091.5 2099.70  5098.6 2105.20  5105.7 2101.76
  5119.8 2108.40  5126.9 2108.31  5134.0 2114.63  5141.0 2112.69  5148.1 2118.87
  5155.1 2117.10  5169.3 2125.25  5176.3 2125.02  5183.4 2129.39  5196.4 2128.51
#Mann=5,-1,0
  4737.1    0.07       0  4936.0    0.16       0  4964.2    0.07       0
  5075.4    0.07       0  5079.4    0.07       0
Bank Sta=5075.4,5079.4
Exp/Cntr=0.3,0.1

Type RM Length L Ch R = 1,7103,49,49,49
BEGIN DESCRIPTION:
Elm 79 7103.395
END DESCRIPTION:
XS GIS Cut Line= 3
      1535705.03      6765088.02      1535908.76      6765239.56
      1536055.04      6765288.01
#Sta/Elev= 30
  4746.1 2136.96  4749.2 2136.96  4753.4 2134.76  4774.2 2128.09  4788.8 2125.84
  4803.4 2121.80  4826.2 2118.34  4832.6 2116.50  4838.9 2115.93  4853.5 2111.77
  4874.3 2107.93  4895.6 2101.68  4924.4 2097.00  4945.5 2091.23  4953.6 2092.54
  4968.2 2093.08  4994.5 2090.55  5035.8 2089.89  5036.1 2089.39  5039.8 2089.89
  5048.7 2094.27  5074.8 2103.87  5080.3 2107.65  5086.4 2109.95  5106.5 2116.94
  5111.9 2121.50  5132.9 2130.53  5138.2 2131.83  5143.5 2135.16  5154.1 2136.55
#Mann=5,-1,0
  4746.1    0.07       0  4826.2    0.16       0  5035.8    0.07       0
  5039.8    0.16       0  5086.4    0.07       0
Bank Sta=5035.8,5039.8
Exp/Cntr=0.3,0.1

Type RM Length L Ch R = 1,7054,65,65,65
BEGIN DESCRIPTION:
Elm 79 7053.69
END DESCRIPTION:
XS GIS Cut Line= 3
      1535668.92      6765155.53      1535908.52      6765290.96
      1536057.81      6765337.83
#Sta/Elev= 30
  4728.9 2130.59  4742.9 2129.27  4748.6 2127.43  4758.8 2126.91  4786.1 2121.13
  4795.4 2117.69  4839.3 2106.14  4873.7 2098.88  4882.9 2096.14  4888.6 2092.68
  4896.7 2091.73  4904.6 2093.49  4919.7 2090.30  4963.8 2090.67  4997.2 2088.75
  4997.5 2088.25  5001.2 2088.75  5021.4 2089.41  5040.7 2098.21  5046.0 2099.63
  5052.8 2104.44  5073.1 2109.66  5078.4 2109.82  5084.3 2113.52  5097.8 2118.19
  5105.2 2120.99  5110.8 2125.28  5116.0 2126.20  5143.2 2136.09  5160.6 2136.44
#Mann=5,-1,0
  4728.9    0.07       0  4795.4    0.16       0  4997.2    0.07       0
  5001.2    0.16       0  5097.8    0.07       0
Bank Sta=4997.2,5001.2
Exp/Cntr=0.3,0.1

Type RM Length L Ch R = 1,6989,45,45,45
BEGIN DESCRIPTION:
Elm 79 6989.13
END DESCRIPTION:
XS GIS Cut Line= 3
      1535674.13      6765219.77      1535905.05      6765353.46
      1536061.53      6765380.97
#Sta/Elev= 30
  4733.0 2118.75  4736.2 2118.75  4739.6 2116.71  4755.8 2118.58  4761.1 2116.08
  4768.7 2116.28  4776.9 2114.91  4782.7 2111.32  4798.4 2106.51  4804.2 2102.76
  4814.2 2100.63  4820.0 2096.24  4826.4 2093.40  4841.5 2090.13  4863.0 2088.71
  4943.4 2088.81  4974.9 2090.53  4988.2 2087.42  4997.4 2086.75  4997.6 2086.25
  5001.4 2086.75  5009.9 2088.06  5030.2 2101.98  5050.2 2107.42  5055.3 2105.75
  5060.7 2109.41  5101.4 2124.99  5121.6 2132.71  5131.8 2134.27  5158.7 2135.68
#Mann=5,-1,0
  4733.0    0.07       0  4755.8    0.16       0  4997.4    0.07       0
  5001.4    0.16       0  5101.4    0.07       0
Bank Sta=4997.4,5001.4
Exp/Cntr=0.3,0.1

Type RM Length L Ch R = 1,6944,83,83,83
BEGIN DESCRIPTION:
Elm 79 6943.94
END DESCRIPTION:
XS GIS Cut Line= 3
      1535627.31      6765336.10      1535898.11      6765396.86
      1536070.82      6765414.13
#Sta/Elev= 30
  4726.3 2140.46  4745.3 2129.07  4753.7 2122.25  4758.8 2124.98  4764.9 2118.69
  4795.7 2097.32  4802.1 2090.75  4807.3 2090.62  4816.2 2087.09  4845.5 2086.91
  4850.6 2086.18  4867.4 2087.52  4899.1 2087.35  4928.9 2088.96  4959.6 2088.80
  4978.1 2085.43  4978.4 2084.93  4982.1 2085.43  5003.8 2086.26  5010.8 2089.12
  5020.8 2091.19  5040.9 2097.59  5060.8 2106.06  5065.8 2105.63  5071.1 2109.41
  5101.2 2119.21  5116.4 2125.49  5141.4 2133.87  5161.3 2134.21  5177.4 2133.25
#Mann=5,-1,0
  4726.3    0.07       0  4745.3    0.16       0  4978.1    0.07       0
  4982.1    0.16       0  5116.4    0.07       0
Bank Sta=4978.1,4982.1
Exp/Cntr=0.3,0.1

Type RM Length L Ch R = 1,6861,64,64,64
BEGIN DESCRIPTION:
Elm 79 6860.7
END DESCRIPTION:
XS GIS Cut Line= 3
      1535658.51      6765386.44      1535840.81      6765457.62
      1536097.74      6765533.49
#Sta/Elev= 30
  4808.4 2134.42  4815.4 2125.88  4823.6 2118.36  4829.0 2120.27  4836.8 2112.48
  4847.6 2105.36  4853.4 2098.91  4858.8 2101.84  4877.9 2087.63  4883.3 2088.98
  4890.5 2086.03  4901.3 2085.59  4986.6 2086.51  5001.7 2083.56  5001.9 2083.06
  5005.7 2083.56  5056.9 2089.10  5062.1 2088.68  5090.2 2092.81  5102.3 2092.43
  5123.2 2095.40  5162.0 2104.26  5195.5 2113.67  5200.5 2115.45  5217.0 2124.54
  5227.4 2126.95  5233.8 2130.23  5248.3 2130.87  5258.7 2127.73  5272.0 2127.55
#Mann=4,-1,0
  4808.4    0.16       0  5001.7    0.07       0  5005.7    0.16       0
  5195.5    0.07       0
Bank Sta=5001.7,5005.7
Exp/Cntr=0.3,0.1

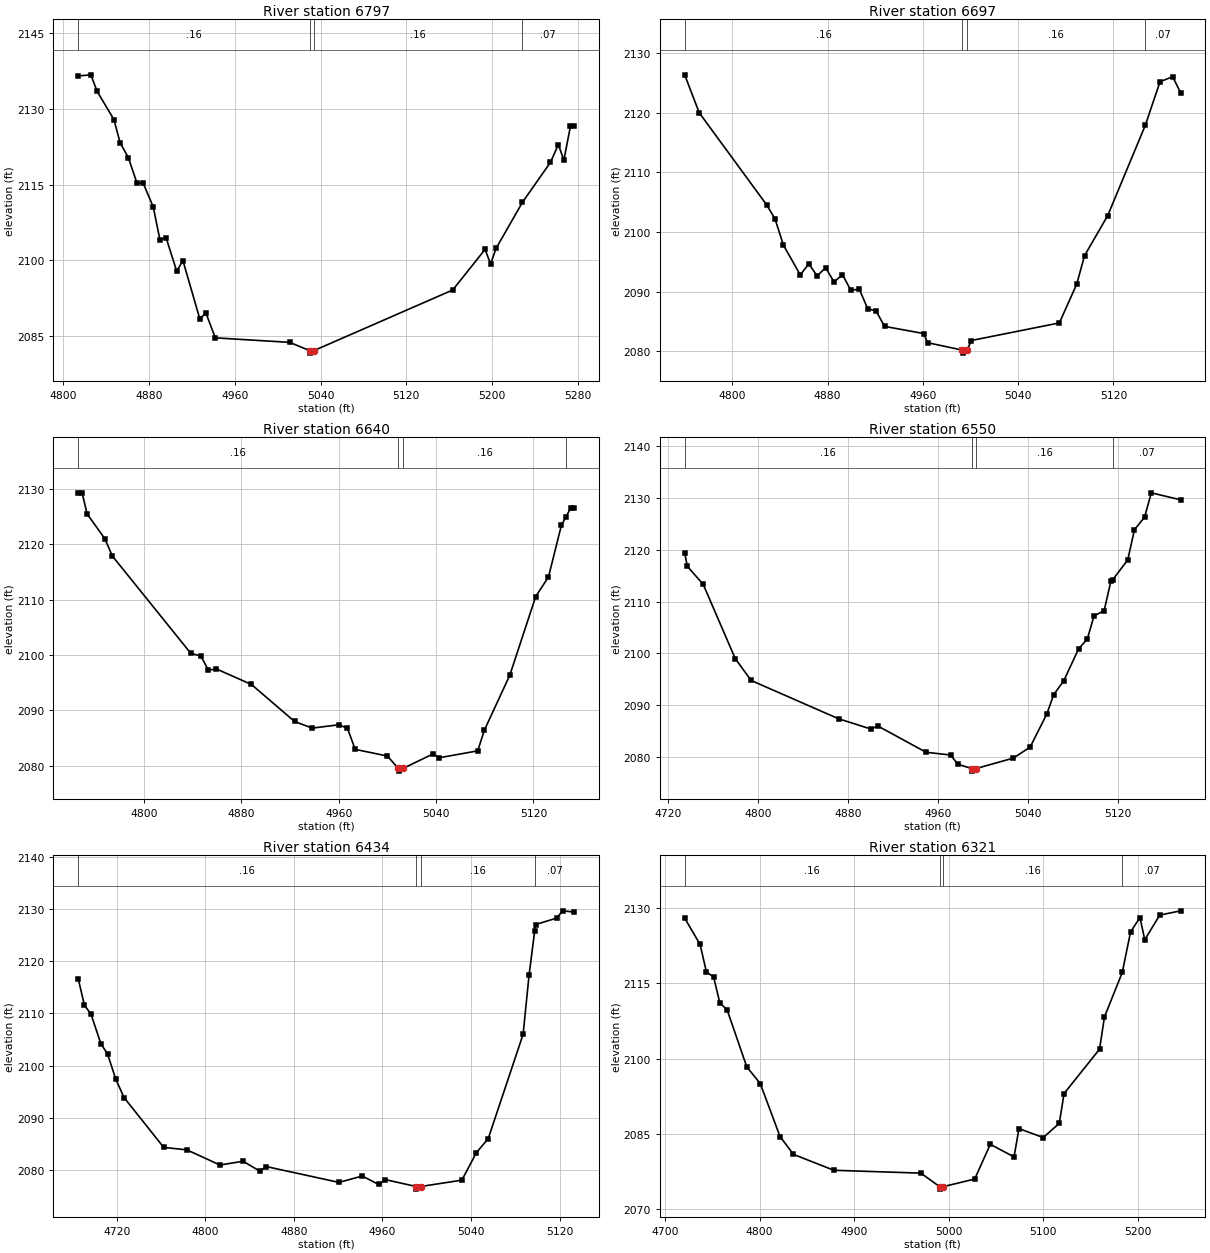
Type RM Length L Ch R = 1,6797,100,100,100
BEGIN DESCRIPTION:
Elm 79 6797.3
END DESCRIPTION:
XS GIS Cut Line= 3
      1535644.63      6765414.22      1535816.51      6765514.92
      1536076.96      6765554.85
#Sta/Elev= 30
  4813.9 2136.51  4825.7 2136.73  4831.5 2133.48  4847.2 2127.88  4853.0 2123.29
  4860.7 2120.34  4868.7 2115.31  4874.5 2115.31  4883.9 2110.60  4890.1 2104.13
  4895.9 2104.49  4905.8 2097.89  4911.6 2099.98  4927.3 2088.47  4933.1 2089.58
  4941.8 2084.69  5011.2 2083.80  5029.8 2082.17  5030.1 2081.67  5033.8 2082.17
  5163.3 2094.16  5193.5 2102.19  5198.6 2099.32  5203.8 2102.41  5228.3 2111.49
  5254.4 2119.39  5261.9 2122.93  5267.0 2119.83  5273.1 2126.52  5276.6 2126.52
#Mann=4,-1,0
  4813.9    0.16       0  5029.8    0.07       0  5033.8    0.16       0
  5228.3    0.07       0
Bank Sta=5029.8,5033.8
Exp/Cntr=0.3,0.1

Type RM Length L Ch R = 1,6697,57,57,57
BEGIN DESCRIPTION:
Elm 79 6696.64
END DESCRIPTION:
XS GIS Cut Line= 3
      1535665.44      6765440.24      1535804.36      6765580.89
      1536011.32      6765651.60
#Sta/Elev= 30
  4760.0 2126.31  4772.2 2119.96  4828.8 2104.54  4835.9 2102.16  4842.9 2097.79
  4857.1 2092.79  4864.2 2094.68  4871.2 2092.62  4878.3 2094.02  4885.4 2091.62
  4892.5 2092.84  4899.5 2090.22  4906.6 2090.42  4913.6 2087.16  4920.8 2086.74
  4927.8 2084.18  4960.7 2082.98  4963.9 2081.45  4993.2 2080.20  4993.5 2079.70
  4997.2 2080.20  5000.6 2081.81  5074.6 2084.76  5089.2 2091.27  5095.7 2096.01
  5115.2 2102.74  5146.8 2117.89  5159.1 2125.15  5169.7 2126.00  5176.4 2123.31
#Mann=4,-1,0
  4760.0    0.16       0  4993.2    0.07       0  4997.2    0.16       0
  5146.8    0.07       0
Bank Sta=4993.2,4997.2
Exp/Cntr=0.3,0.1

Type RM Length L Ch R = 1,6640,90,90,90
BEGIN DESCRIPTION:
Elm 79 6639.588
END DESCRIPTION:
XS GIS Cut Line= 3
      1535654.99      6765437.98      1535809.42      6765639.64
      1535955.00      6765688.00
#Sta/Elev= 30
  4746.0 2129.35  4749.2 2129.35  4753.3 2125.53  4767.8 2121.07  4774.1 2117.90
  4838.5 2100.30  4846.7 2099.82  4853.0 2097.25  4859.4 2097.49  4888.3 2094.67
  4923.7 2087.98  4938.2 2086.77  4960.1 2087.38  4967.2 2086.74  4973.5 2082.93
  5000.0 2081.72  5008.9 2079.49  5009.2 2078.99  5012.9 2079.49  5037.3 2082.08
  5042.6 2081.41  5074.2 2082.66  5079.6 2086.38  5100.6 2096.38  5121.8 2110.58
  5132.3 2114.12  5142.9 2123.46  5146.6 2124.97  5150.8 2126.69  5153.4 2126.69
#Mann=4,-1,0
  4746.0    0.16       0  5008.9    0.07       0  5012.9    0.16       0
  5146.6    0.07       0
Bank Sta=5008.9,5012.9
Exp/Cntr=0.3,0.1

Type RM Length L Ch R = 1,6550,116,116,116
BEGIN DESCRIPTION:
Elm 79 6550.01
END DESCRIPTION:
XS GIS Cut Line= 3
      1535599.48      6765520.11      1535776.58      6765721.51
      1535920.33      6765818.50
#Sta/Elev= 30
  4734.6 2119.43  4736.9 2116.81  4751.1 2113.32  4779.6 2099.01  4793.8 2094.78
  4871.6 2087.40  4900.1 2085.44  4906.8 2085.98  4949.5 2080.94  4971.3 2080.41
  4977.9 2078.63  4990.1 2077.80  4990.4 2077.30  4994.1 2077.80  5027.2 2079.81
  5042.2 2081.93  5057.1 2088.33  5063.2 2092.06  5072.1 2094.70  5085.3 2100.86
  5093.1 2102.77  5099.1 2107.24  5108.1 2108.24  5114.1 2113.91  5115.7 2114.20
  5129.1 2118.03  5135.1 2123.86  5144.1 2126.28  5150.1 2130.97  5176.2 2129.62
#Mann=4,-1,0
  4734.6    0.16       0  4990.1    0.07       0  4994.1    0.16       0
  5115.7    0.07       0
Bank Sta=4990.1,4994.1
Exp/Cntr=0.3,0.1

Type RM Length L Ch R = 1,6434,113,113,113
BEGIN DESCRIPTION:
Elm 79 6434.36
END DESCRIPTION:
XS GIS Cut Line= 3
      1535545.70      6765560.09      1535726.23      6765822.21
      1535847.75      6765867.34
#Sta/Elev= 30
  4685.2 2116.65  4690.8 2111.59  4696.8 2109.83  4705.6 2104.23  4711.7 2102.23
  4719.1 2097.43  4726.6 2093.88  4762.4 2084.34  4783.4 2083.86  4813.2 2080.96
  4834.1 2081.68  4849.0 2079.81  4855.1 2080.66  4920.7 2077.63  4941.7 2078.85
  4956.5 2077.24  4962.6 2078.16  4990.4 2076.84  4990.6 2076.34  4994.4 2076.84
  5031.7 2078.06  5044.8 2083.33  5055.5 2086.02  5087.0 2106.01  5092.4 2117.39
  5097.5 2125.86  5098.2 2127.02  5117.4 2128.28  5122.7 2129.66  5133.1 2129.42
#Mann=4,-1,0
  4685.2    0.16       0  4990.4    0.07       0  4994.4    0.16       0
  5097.5    0.07       0
Bank Sta=4990.4,4994.4
Exp/Cntr=0.3,0.1

Type RM Length L Ch R = 1,6321,102,102,102
BEGIN DESCRIPTION:
Elm 79 6320.79
END DESCRIPTION:
XS GIS Cut Line= 3
      1535446.75      6765603.49      1535661.99      6765846.51
      1535856.48      6765891.66
#Sta/Elev= 30
  4720.8 2127.94  4737.1 2122.70  4743.8 2117.22  4751.4 2116.23  4758.0 2111.04
  4765.6 2109.74  4786.5 2098.34  4800.7 2095.05  4821.6 2084.51  4835.8 2080.96
  4878.5 2077.80  4970.5 2077.23  4990.3 2074.55  4990.5 2074.05  4994.3 2074.55
  5027.4 2076.06  5043.9 2082.96  5069.0 2080.46  5074.2 2086.09  5099.9 2084.30
  5116.8 2087.13  5121.9 2093.06  5159.4 2101.88  5164.6 2108.29  5183.4 2117.13
  5192.2 2125.21  5202.1 2128.05  5207.2 2123.64  5223.0 2128.54  5245.1 2129.39
#Mann=4,-1,0
  4720.8    0.16       0  4990.3    0.07       0  4994.3    0.16       0
  5183.4    0.07       0
Bank Sta=4990.3,4994.3
Exp/Cntr=0.3,0.1