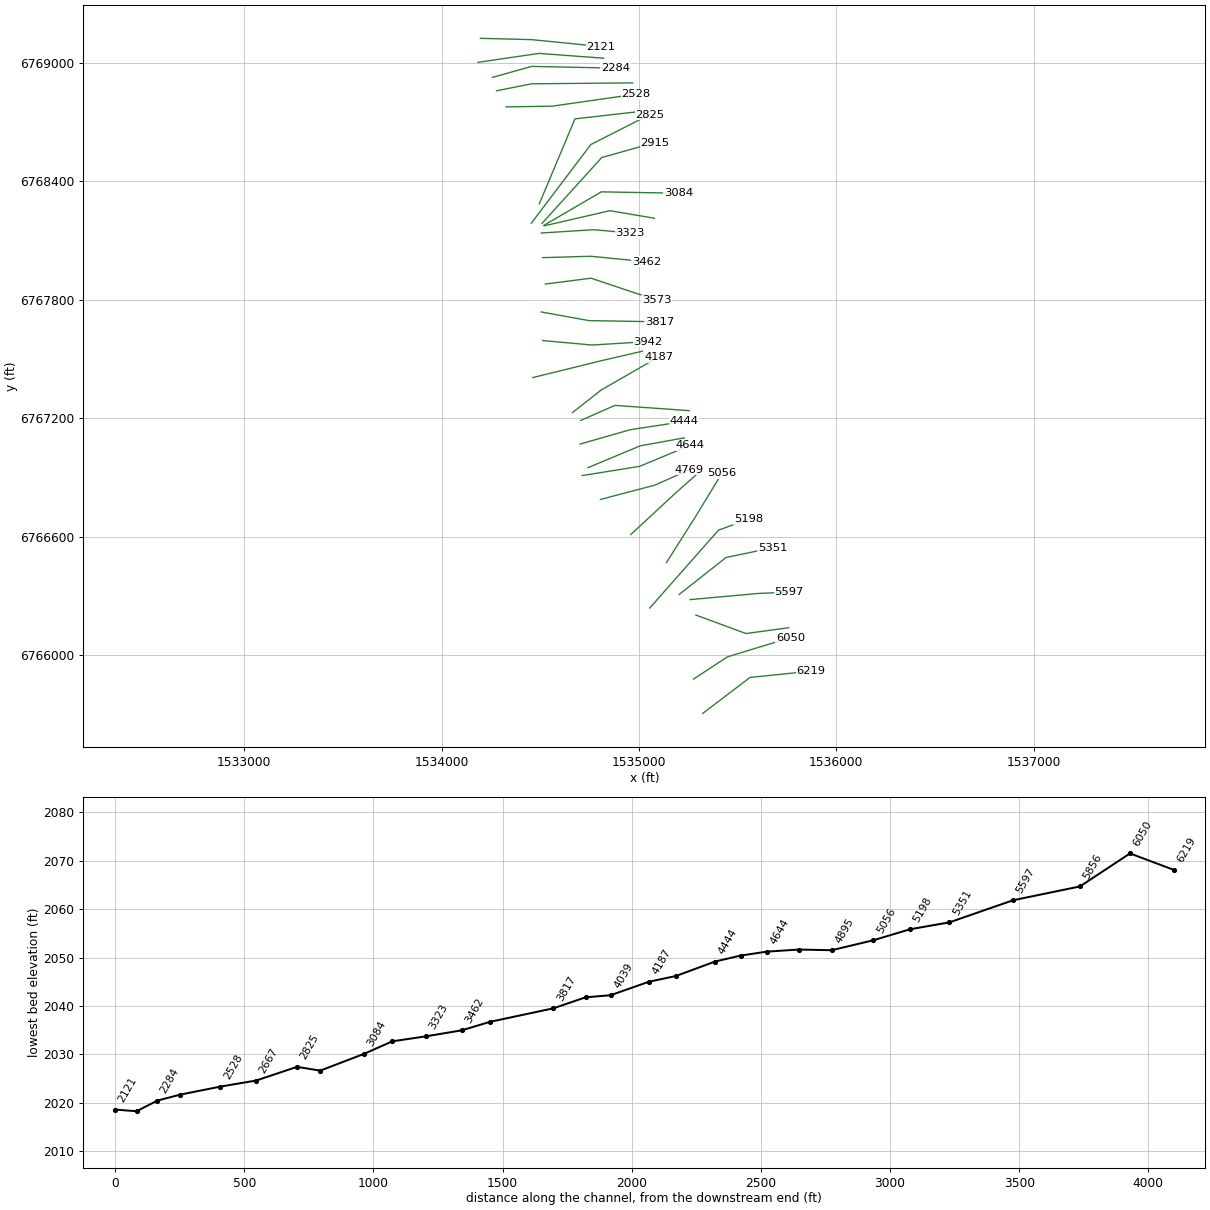
HEC-RAS study Elm 79.prj: Elm 79 Base Level Engineering

--- Elm 79.g01 (geometry) --- (continued)

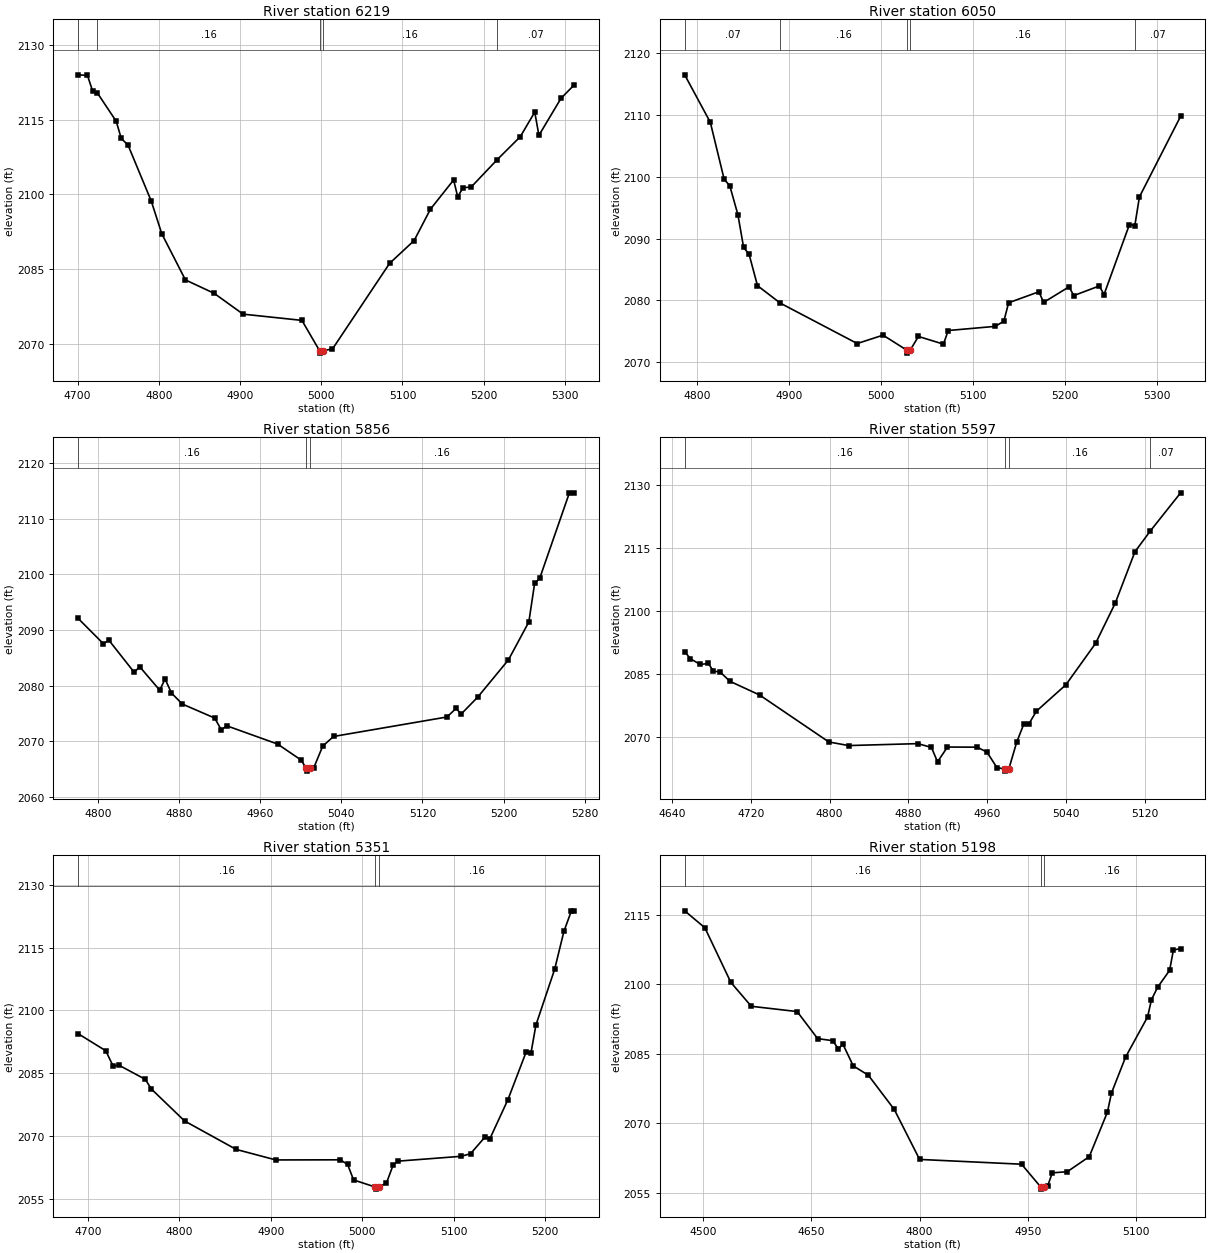
Type RM Length L Ch R = 1,6219,169,169,169
BEGIN DESCRIPTION:
Elm 79 6219.35
END DESCRIPTION:
XS GIS Cut Line= 3
      1535323.48      6765704.17      1535563.04      6765886.44
      1535871.05      6765917.59
#Sta/Elev= 30
  4700.8 2124.02  4712.2 2123.90  4718.5 2120.77  4724.4 2120.38  4747.6 2114.68
  4753.8 2111.23  4762.1 2109.92  4790.7 2098.67  4803.7 2092.09  4832.8 2082.82
  4868.2 2080.12  4903.8 2075.94  4976.2 2074.69  4997.9 2068.61  4998.2 2068.11
  5001.9 2068.61  5013.8 2068.93  5084.2 2086.15  5114.4 2090.73  5134.5 2097.04
  5163.0 2102.90  5168.0 2099.54  5174.7 2101.33  5184.7 2101.49  5216.6 2106.97
  5245.0 2111.58  5262.9 2116.53  5268.0 2111.86  5295.3 2119.32  5311.4 2121.98
#Mann=5,-1,0
  4700.8    0.07       0  4724.4    0.16       0  4997.9    0.07       0
  5001.9    0.16       0  5216.6    0.07       0
Bank Sta=4997.9,5001.9
Exp/Cntr=0.3,0.1

Type RM Length L Ch R = 1,6050,194,194,194
BEGIN DESCRIPTION:
Elm 79 6050.17
END DESCRIPTION:
XS GIS Cut Line= 3
      1535276.56      6765877.75      1535448.45      6765990.61
      1535767.86      6766087.82
#Sta/Elev= 30
  4786.6 2116.42  4814.5 2108.75  4829.6 2099.53  4835.6 2098.55  4844.5 2093.84
  4850.7 2088.56  4856.7 2087.43  4865.8 2082.39  4890.6 2079.57  4974.3 2073.05
  5002.4 2074.40  5028.0 2072.00  5028.2 2071.50  5032.0 2072.00  5040.9 2074.19
  5068.1 2072.95  5073.3 2075.15  5124.5 2075.82  5133.8 2076.66  5139.0 2079.63
  5171.9 2081.40  5177.1 2079.69  5204.7 2082.20  5209.9 2080.79  5237.6 2082.34
  5242.8 2080.96  5270.4 2092.25  5276.3 2092.10  5281.3 2096.72  5326.1 2109.73
#Mann=5,-1,0
  4786.6    0.07       0  4890.6    0.16       0  5028.0    0.07       0
  5032.0    0.16       0  5276.3    0.07       0
Bank Sta=5028,5032
Exp/Cntr=0.3,0.1

Type RM Length L Ch R = 1,5856,259,259,259
BEGIN DESCRIPTION:
Elm 79 5855.92
END DESCRIPTION:
XS GIS Cut Line= 3
      1535288.73      6766202.41      1535542.20      6766108.67
      1535759.25      6766138.18
#Sta/Elev= 30
  4780.4 2092.08  4805.3 2087.53  4810.6 2088.19  4835.7 2082.40  4841.0 2083.43
  4860.8 2079.21  4866.1 2081.21  4872.4 2078.70  4883.0 2076.73  4915.0 2074.21
  4921.6 2072.09  4926.9 2072.82  4977.1 2069.54  5000.3 2066.67  5005.4 2065.18
  5005.7 2064.68  5009.5 2065.18  5012.8 2065.27  5021.6 2069.16  5032.3 2070.90
  5144.3 2074.40  5153.2 2075.95  5158.2 2074.92  5174.6 2077.97  5204.9 2084.66
  5225.0 2091.46  5230.7 2098.38  5235.7 2099.28  5265.0 2114.63  5269.7 2114.63
#Mann=3,-1,0
  4780.4    0.16       0  5005.4    0.07       0  5009.5    0.16       0
Bank Sta=5005.4,5009.5
Exp/Cntr=0.3,0.1

Type RM Length L Ch R = 1,5597,246,246,246
BEGIN DESCRIPTION:
Elm 79 5596.78
END DESCRIPTION:
XS GIS Cut Line= 3
      1535259.21      6766280.54      1535604.70      6766311.79
      1535761.35      6766318.68
#Sta/Elev= 30
  4652.9 2090.28  4658.7 2088.56  4668.8 2087.20  4677.0 2087.44  4682.0 2085.61
  4688.8 2085.43  4698.9 2083.19  4729.0 2079.94  4799.3 2068.77  4819.4 2067.91
  4889.7 2068.37  4903.5 2067.47  4909.7 2064.05  4919.8 2067.56  4949.9 2067.53
  4959.9 2066.36  4970.0 2062.68  4978.0 2062.33  4978.2 2061.83  4982.1 2062.33
  4990.1 2068.71  4997.4 2073.07  5002.5 2073.07  5010.1 2076.08  5040.1 2082.38
  5070.2 2092.21  5090.2 2101.79  5110.2 2114.01  5125.9 2118.98  5156.6 2128.03
#Mann=4,-1,0
  4652.9    0.16       0  4978.0    0.07       0  4982.1    0.16       0
  5125.9    0.07       0
Bank Sta=4978,4982.1
Exp/Cntr=0.3,0.1

Type RM Length L Ch R = 1,5351,153,153,153
BEGIN DESCRIPTION:
Elm 79 5351.05
END DESCRIPTION:
XS GIS Cut Line= 3
      1535203.63      6766306.56      1535441.51      6766494.08
      1535675.92      6766542.70
#Sta/Elev= 30
  4689.6 2094.43  4719.7 2090.36  4727.7 2086.73  4734.1 2086.91  4763.0 2083.52
  4769.4 2081.25  4805.9 2073.57  4862.4 2066.76  4905.7 2064.25  4976.2 2064.28
  4984.2 2063.16  4990.7 2059.47  5014.4 2057.77  5014.7 2057.27  5018.5 2057.77
  5026.7 2058.75  5034.1 2063.11  5039.2 2063.96  5108.4 2065.12  5118.6 2065.74
  5134.4 2069.72  5139.5 2069.20  5159.5 2078.68  5179.5 2090.12  5184.6 2089.72
  5190.1 2096.51  5210.5 2109.79  5220.7 2118.90  5228.9 2123.82  5231.9 2123.82
#Mann=3,-1,0
  4689.6    0.16       0  5014.4    0.07       0  5018.5    0.16       0
Bank Sta=5014.4,5018.5
Exp/Cntr=0.3,0.1

Type RM Length L Ch R = 1,5198,142,142,142
BEGIN DESCRIPTION:
Elm 79 5198.259
END DESCRIPTION:
XS GIS Cut Line= 3
      1535055.03      6766238.03      1535402.92      6766632.29
      1535555.04      6766688.01
#Sta/Elev= 30
  4474.2 2115.81  4502.2 2112.16  4538.2 2100.40  4566.6 2095.24  4630.2 2094.10
  4658.6 2088.27  4679.5 2087.83  4687.1 2086.12  4693.8 2087.03  4708.0 2082.39
  4728.9 2080.39  4764.9 2073.00  4800.0 2062.24  4941.4 2061.21  4967.8 2056.34
  4968.0 2055.84  4971.9 2056.34  4977.4 2056.41  4984.0 2059.35  5004.8 2059.59
  5035.3 2062.84  5060.5 2072.44  5066.1 2076.55  5085.7 2084.30  5116.2 2092.95
  5121.5 2096.62  5130.0 2099.32  5146.7 2102.97  5152.0 2107.37  5162.0 2107.68
#Mann=3,-1,0
  4474.2    0.16       0  4967.8    0.07       0  4971.9    0.16       0
Bank Sta=4967.8,4971.9
Exp/Cntr=0.3,0.1

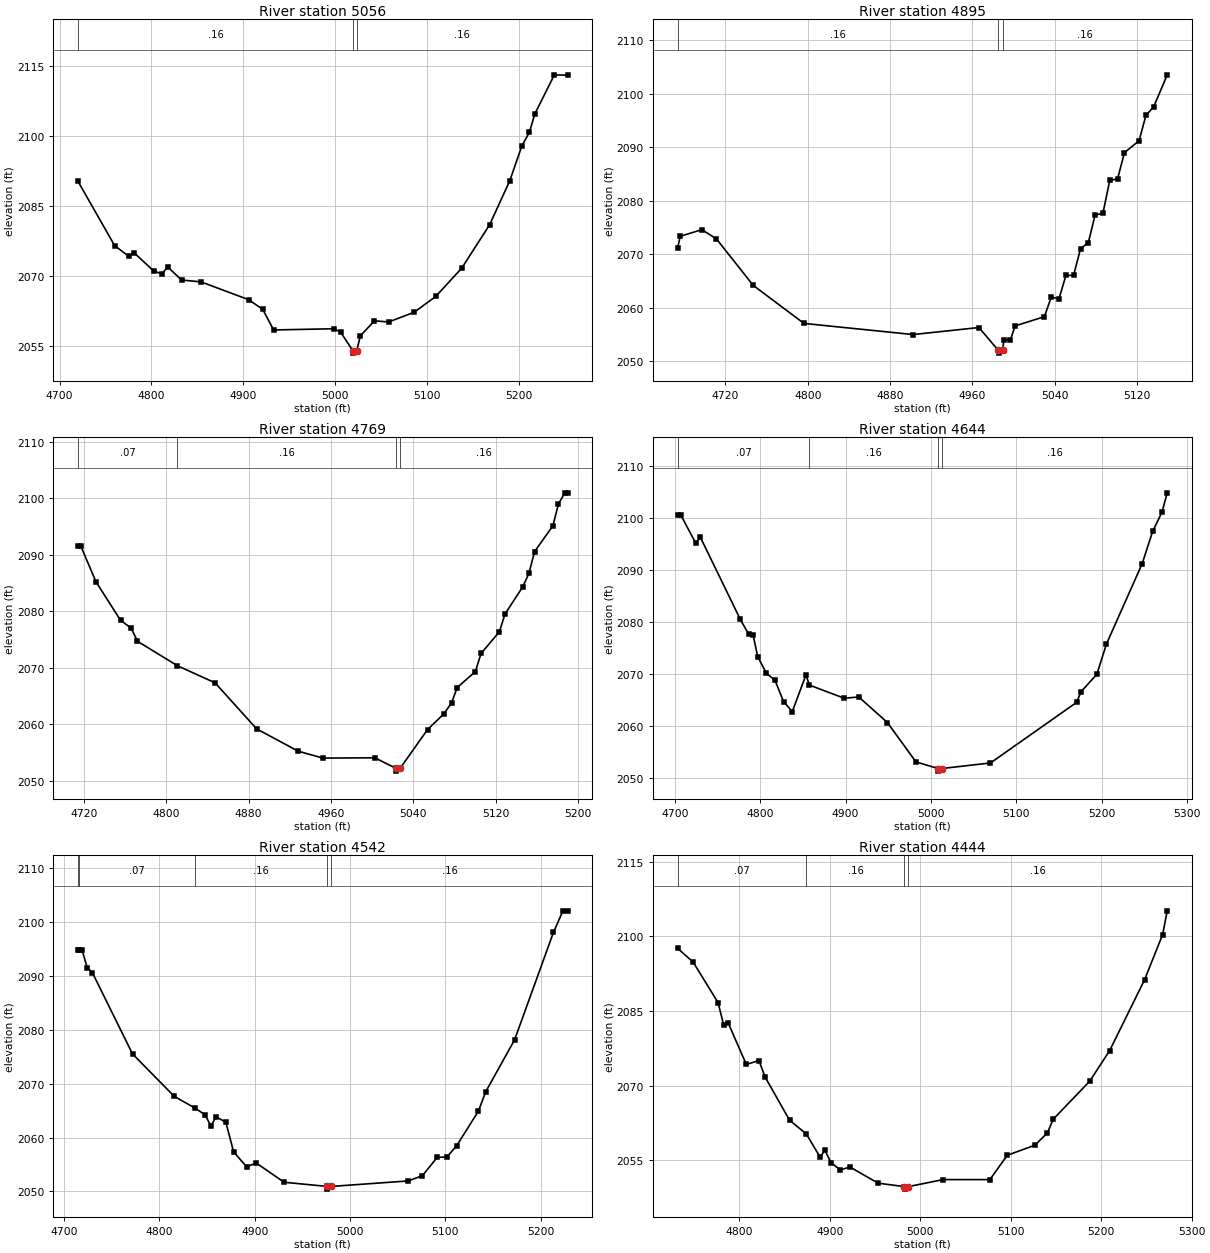
Type RM Length L Ch R = 1,5056,161,161,161
BEGIN DESCRIPTION:
Elm 79 5056.29
END DESCRIPTION:
XS GIS Cut Line= 3
      1535139.45      6766468.07      1535288.73      6766704.15
      1535420.31      6766920.57
#Sta/Elev= 30
  4720.0 2090.31  4759.9 2076.56  4775.2 2074.25  4781.1 2075.01  4802.7 2071.06
  4811.6 2070.52  4817.5 2072.01  4832.8 2069.19  4854.0 2068.79  4905.7 2064.99
  4921.0 2062.92  4932.9 2058.52  4998.6 2058.78  5005.7 2058.04  5019.1 2054.07
  5019.4 2053.57  5023.2 2054.07  5027.2 2057.26  5042.5 2060.47  5058.0 2060.23
  5085.7 2062.30  5109.2 2065.68  5137.5 2071.74  5167.7 2080.97  5189.7 2090.39
  5202.8 2097.82  5211.1 2100.78  5216.9 2104.66  5238.2 2113.03  5252.6 2112.94
#Mann=3,-1,0
  4720.0    0.16       0  5019.1    0.07       0  5023.2    0.16       0
Bank Sta=5019.1,5023.2
Exp/Cntr=0.3,0.1

Type RM Length L Ch R = 1,4895,126,126,126
BEGIN DESCRIPTION:
Elm 79 4894.9
END DESCRIPTION:
XS GIS Cut Line= 3
      1534958.87      6766610.40      1535193.24      6766827.42
      1535310.65      6766931.01
#Sta/Elev= 30
  4673.4 2071.13  4676.1 2073.35  4697.1 2074.58  4711.2 2072.86  4747.0 2064.17
  4796.3 2057.07  4902.3 2054.99  4966.4 2056.30  4985.3 2052.02  4985.6 2051.52
  4989.4 2052.02  4990.6 2053.99  4997.0 2053.99  5001.5 2056.60  5030.0 2058.33
  5036.7 2062.00  5044.2 2061.66  5050.9 2066.02  5058.4 2066.06  5065.1 2071.01
  5072.7 2072.16  5079.3 2077.32  5086.9 2077.64  5093.6 2083.83  5101.1 2084.04
  5107.8 2088.97  5122.0 2091.18  5128.7 2095.93  5136.2 2097.51  5149.4 2103.50
#Mann=3,-1,0
  4673.4    0.16       0  4985.3    0.07       0  4989.4    0.16       0
Bank Sta=4985.3,4989.4
Exp/Cntr=0.3,0.1

Type RM Length L Ch R = 1,4769,125,125,125
BEGIN DESCRIPTION:
Elm 79 4769.174
END DESCRIPTION:
XS GIS Cut Line= 3
      1534804.98      6766787.99      1535081.44      6766860.86
      1535254.97      6766937.99
#Sta/Elev= 30
  4714.1 2091.59  4716.7 2091.59  4731.7 2085.17  4755.5 2078.37  4765.8 2076.99
  4772.0 2074.65  4810.8 2070.32  4847.4 2067.29  4887.7 2059.15  4928.0 2055.20
  4952.0 2053.97  5002.6 2054.02  5023.0 2052.16  5023.3 2051.66  5027.2 2052.16
  5053.8 2059.02  5069.6 2061.79  5077.1 2063.73  5082.6 2066.46  5100.3 2069.29
  5105.8 2072.49  5123.6 2076.33  5129.1 2079.48  5146.2 2084.26  5152.3 2086.66
  5157.8 2090.52  5175.6 2095.10  5181.0 2098.95  5187.2 2100.93  5189.9 2100.93
#Mann=4,-1,0
  4714.1    0.07       0  4810.8    0.16       0  5023.0    0.07       0
  5027.2    0.16       0
Bank Sta=5023,5027.2
Exp/Cntr=0.3,0.1

Type RM Length L Ch R = 1,4644,102,102,102
BEGIN DESCRIPTION:
Elm 79 4644.41
END DESCRIPTION:
XS GIS Cut Line= 3
      1534712.33      6766909.01      1535004.01      6766955.89
      1535260.74      6767062.72
#Sta/Elev= 30
  4703.2 2100.50  4707.1 2100.50  4724.7 2095.05  4729.8 2096.28  4776.8 2080.42
  4786.6 2077.56  4791.7 2077.43  4797.1 2073.28  4807.2 2070.07  4817.3 2068.73
  4827.4 2064.61  4837.6 2062.70  4853.6 2069.73  4857.7 2067.79  4898.3 2065.26
  4915.5 2065.50  4949.0 2060.58  4982.4 2053.01  5008.4 2051.73  5008.7 2051.23
  5012.6 2051.73  5069.7 2052.80  5170.5 2064.45  5175.9 2066.54  5194.3 2069.87
  5205.5 2075.69  5247.4 2091.17  5259.6 2097.35  5270.5 2101.05  5276.7 2104.79
#Mann=4,-1,0
  4703.2    0.07       0  4857.7    0.16       0  5008.4    0.07       0
  5012.6    0.16       0
Bank Sta=5008.4,5012.6
Exp/Cntr=0.3,0.1

Type RM Length L Ch R = 1,4542,98,98,98
BEGIN DESCRIPTION:
Elm 79 4541.68
END DESCRIPTION:
XS GIS Cut Line= 3
      1534741.84      6766948.94      1535007.48      6767060.05
      1535229.68      6767099.98
#Sta/Elev= 30
  4714.5 2094.84  4715.9 2094.84  4718.9 2094.84  4724.2 2091.58  4729.6 2090.66
  4771.8 2075.53  4815.5 2067.66  4837.0 2065.50  4848.0 2064.21  4854.0 2062.12
  4859.4 2063.86  4869.7 2062.83  4877.8 2057.36  4891.4 2054.56  4901.6 2055.26
  4930.8 2051.69  4976.0 2050.91  4976.3 2050.41  4980.2 2050.91  5060.9 2051.93
  5075.9 2052.91  5091.4 2056.32  5101.5 2056.38  5111.7 2058.44  5134.6 2064.89
  5142.2 2068.48  5172.6 2078.16  5213.3 2098.10  5223.3 2102.12  5228.2 2102.12
#Mann=5,-1,0
  4714.5    0.16       0  4715.9    0.07       0  4837.0    0.16       0
  4976.0    0.07       0  4980.2    0.16       0
Bank Sta=4976,4980.2
Exp/Cntr=0.3,0.1

Type RM Length L Ch R = 1,4444,152,152,152
BEGIN DESCRIPTION:
Elm 79 4443.94
END DESCRIPTION:
XS GIS Cut Line= 3
      1534701.92      6767068.73      1534957.13      6767141.65
      1535229.68      6767183.05
#Sta/Elev= 30
  4731.9 2097.58  4749.1 2094.83  4776.7 2086.67  4782.9 2082.17  4788.1 2082.50
  4807.9 2074.24  4821.9 2075.02  4828.7 2071.71  4855.7 2063.04  4874.3 2060.26
  4889.5 2055.60  4894.7 2057.00  4901.5 2054.50  4911.9 2053.03  4922.3 2053.65
  4953.5 2050.39  4982.6 2049.69  4982.9 2049.19  4986.8 2049.69  5025.5 2051.11
  5077.0 2051.10  5096.3 2056.00  5126.7 2058.01  5140.7 2060.51  5146.9 2063.22
  5187.3 2070.86  5209.4 2077.03  5248.0 2091.27  5267.9 2100.34  5273.0 2105.11
#Mann=4,-1,0
  4731.9    0.07       0  4874.3    0.16       0  4982.6    0.07       0
  4986.8    0.16       0
Bank Sta=4982.6,4986.8
Exp/Cntr=0.3,0.1

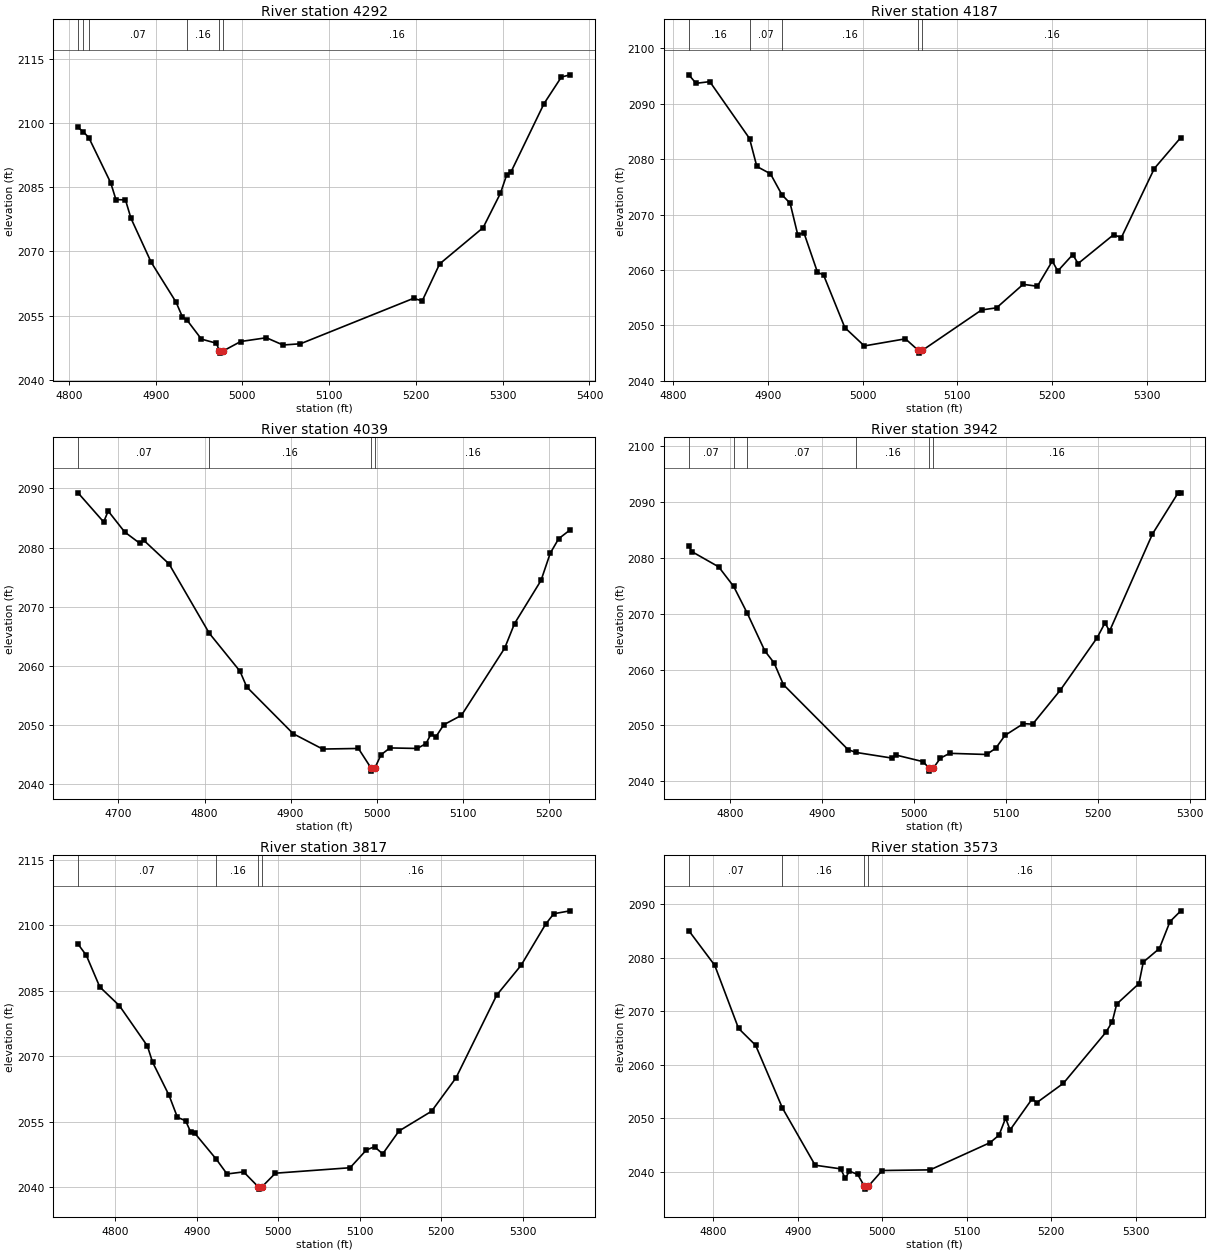
Type RM Length L Ch R = 1,4292,105,105,105
BEGIN DESCRIPTION:
Elm 79 4291.707
END DESCRIPTION:
XS GIS Cut Line= 3
      1534704.99      6767188.00      1534878.30      6767264.65
      1535254.96      6767238.00
#Sta/Elev= 30
  4810.5 2099.01  4816.5 2098.02  4822.9 2096.65  4848.2 2086.05  4854.2 2082.13
  4865.2 2082.06  4871.5 2077.77  4894.8 2067.47  4923.5 2058.13  4930.8 2054.69
  4936.3 2053.88  4952.7 2049.48  4970.1 2048.51  4973.4 2046.70  4973.7 2046.20
  4977.7 2046.70  4998.0 2048.92  5027.6 2049.80  5046.8 2048.10  5066.9 2048.39
  5197.2 2059.02  5207.2 2058.42  5227.3 2067.08  5277.4 2075.56  5297.4 2083.62
  5304.6 2087.95  5309.6 2088.63  5347.6 2104.59  5367.6 2110.81  5377.6 2111.33
#Mann=6,-1,0
  4810.5    0.07       0  4816.5    0.16       0  4822.9    0.07       0
  4936.3    0.16       0  4973.4    0.07       0  4977.7    0.16       0
Bank Sta=4973.4,4977.7
Exp/Cntr=0.3,0.1

Type RM Length L Ch R = 1,4187,148,148,148
BEGIN DESCRIPTION:
Elm 79 4186.7
END DESCRIPTION:
XS GIS Cut Line= 3
      1534663.70      6767228.43      1534809.56      6767343.04
      1535099.47      6767509.69
#Sta/Elev= 30
  4816.3 2095.21  4824.0 2093.68  4838.5 2093.98  4880.5 2083.72  4888.2 2078.68
  4902.6 2077.36  4914.7 2073.58  4923.4 2072.03  4931.5 2066.32  4937.9 2066.75
  4952.3 2059.59  4958.7 2059.11  4981.2 2049.61  5001.8 2046.31  5045.2 2047.59
  5058.8 2045.51  5059.1 2045.01  5063.1 2045.51  5125.7 2052.80  5141.5 2053.18
  5169.6 2057.42  5184.6 2057.07  5200.4 2061.61  5206.2 2059.82  5222.0 2062.78
  5227.7 2061.17  5265.1 2066.36  5273.4 2065.86  5308.2 2078.31  5336.2 2083.90
#Mann=5,-1,0
  4816.3    0.16       0  4880.5    0.07       0  4914.7    0.16       0
  5058.8    0.07       0  5063.1    0.16       0
Bank Sta=5058.8,5063.1
Exp/Cntr=0.3,0.1

Type RM Length L Ch R = 1,4039,97,97,97
BEGIN DESCRIPTION:
Elm 79 4038.95
END DESCRIPTION:
XS GIS Cut Line= 3
      1534462.34      6767405.54      1534807.83      6767490.61
      1535017.87      6767539.21
#Sta/Elev= 30
  4653.1 2089.25  4682.9 2084.32  4688.1 2086.18  4707.3 2082.63  4724.5 2080.76
  4729.6 2081.21  4758.8 2077.24  4805.5 2065.53  4841.2 2059.11  4849.0 2056.46
  4903.0 2048.55  4937.2 2045.96  4978.7 2046.06  4993.5 2042.73  4993.8 2042.23
  4997.8 2042.73  5004.9 2044.98  5015.3 2046.15  5047.1 2046.06  5057.3 2046.89
  5063.2 2048.57  5068.3 2047.95  5077.9 2050.07  5098.4 2051.66  5148.6 2063.01
  5160.0 2067.15  5190.8 2074.45  5201.5 2079.05  5211.3 2081.50  5224.5 2082.98
#Mann=4,-1,0
  4653.1    0.07       0  4805.5    0.16       0  4993.5    0.07       0
  4997.8    0.16       0
Bank Sta=4993.5,4997.8
Exp/Cntr=0.3,0.1

Type RM Length L Ch R = 1,3942,125,125,125
BEGIN DESCRIPTION:
Elm 79 3941.79
END DESCRIPTION:
XS GIS Cut Line= 3
      1534512.65      6767593.04      1534762.69      6767570.47
      1535045.70      6767587.83
#Sta/Elev= 30
  4755.1 2082.04  4759.0 2081.06  4787.6 2078.38  4803.9 2074.87  4818.7 2070.06
  4837.8 2063.31  4847.8 2061.18  4857.9 2057.29  4928.1 2045.66  4936.4 2045.16
  4975.7 2044.14  4980.7 2044.66  5009.8 2043.49  5016.3 2042.30  5016.6 2041.80
  5020.6 2042.30  5028.5 2044.12  5038.5 2044.99  5078.6 2044.78  5088.6 2045.89
  5098.6 2048.19  5118.7 2050.31  5128.7 2050.21  5158.8 2056.31  5198.8 2065.69
  5207.3 2068.35  5212.3 2066.88  5258.9 2084.27  5286.8 2091.64  5289.7 2091.64
#Mann=6,-1,0
  4755.1    0.07       0  4803.9    0.16       0  4818.7    0.07       0
  4936.4    0.16       0  5016.3    0.07       0  5020.6    0.16       0
Bank Sta=5016.3,5020.6
Exp/Cntr=0.3,0.1

Type RM Length L Ch R = 1,3817,244,244,244
BEGIN DESCRIPTION:
Elm 79 3817.334
END DESCRIPTION:
XS GIS Cut Line= 3
      1534505.01      6767738.00      1534746.85      6767694.06
      1535105.00      6767688.00
#Sta/Elev= 30
  4754.2 2095.65  4764.4 2093.07  4780.9 2085.84  4805.0 2081.54  4839.3 2072.33
  4845.7 2068.61  4866.0 2060.98  4876.2 2055.98  4886.3 2055.18  4892.7 2052.51
  4897.8 2052.27  4924.1 2046.33  4937.1 2042.99  4957.5 2043.47  4975.6 2040.02
  4975.9 2039.52  4979.9 2040.02  4996.5 2043.17  5088.2 2044.42  5108.2 2048.49
  5118.2 2049.23  5128.2 2047.59  5148.2 2052.83  5188.2 2057.36  5218.2 2065.01
  5268.2 2083.97  5298.2 2090.82  5328.2 2100.20  5338.2 2102.60  5358.2 2103.27
#Mann=4,-1,0
  4754.2    0.07       0  4924.1    0.16       0  4975.6    0.07       0
  4979.9    0.16       0
Bank Sta=4975.6,4979.9
Exp/Cntr=0.3,0.1

Type RM Length L Ch R = 1,3573,111,111,111
BEGIN DESCRIPTION:
Elm 79 3573.05
END DESCRIPTION:
XS GIS Cut Line= 3
      1534526.57      6767879.50      1534757.48      6767909.01
      1535089.07      6767797.90
#Sta/Elev= 30
  4770.9 2085.08  4801.6 2078.60  4829.8 2066.80  4850.0 2063.65  4881.8 2051.90
  4920.5 2041.22  4950.8 2040.54  4956.1 2038.75  4961.1 2040.11  4970.9 2039.49
  4978.9 2037.25  4979.2 2036.75  4983.2 2037.25  4999.9 2040.23  5056.6 2040.35
  5127.6 2045.44  5138.2 2046.85  5146.0 2050.02  5151.3 2047.82  5177.5 2053.65
  5182.8 2052.91  5214.4 2056.54  5264.7 2066.07  5272.2 2068.03  5277.5 2071.35
  5303.8 2075.17  5309.0 2079.20  5328.0 2081.73  5340.6 2086.77  5353.4 2088.78
#Mann=4,-1,0
  4770.9    0.07       0  4881.8    0.16       0  4978.9    0.07       0
  4983.2    0.16       0
Bank Sta=4978.9,4983.2
Exp/Cntr=0.3,0.1

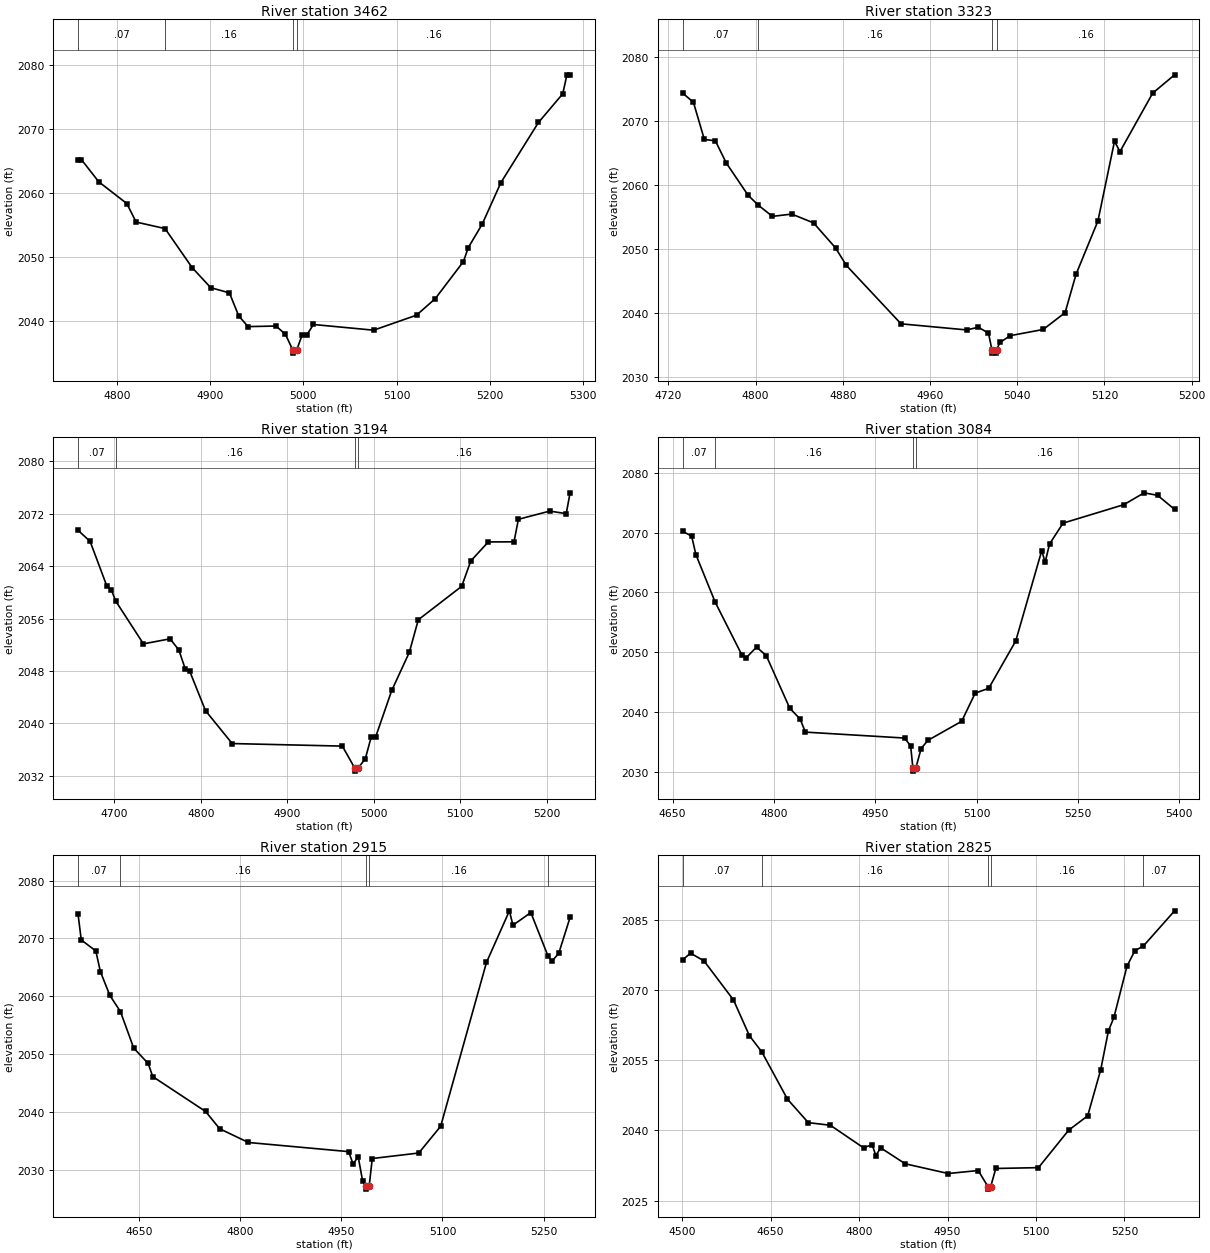
Type RM Length L Ch R = 1,3462,139,139,139
BEGIN DESCRIPTION:
Elm 79 3461.51
END DESCRIPTION:
XS GIS Cut Line= 3
      1534512.74      6768013.18      1534755.74      6768020.12
      1535038.78      6767992.34
#Sta/Elev= 30
  4758.4 2065.27  4762.0 2065.27  4780.7 2061.78  4810.7 2058.39  4820.7 2055.49
  4851.7 2054.47  4880.7 2048.37  4900.7 2045.22  4920.7 2044.41  4930.7 2040.80
  4940.7 2039.13  4970.7 2039.22  4980.8 2037.91  4988.6 2035.48  4988.9 2034.98
  4992.9 2035.48  4998.6 2037.81  5003.6 2037.81  5010.8 2039.46  5075.3 2038.57
  5121.3 2040.92  5141.4 2043.51  5171.6 2049.31  5176.7 2051.47  5191.7 2055.16
  5211.8 2061.68  5252.0 2071.07  5278.1 2075.57  5282.5 2078.53  5285.9 2078.53
#Mann=4,-1,0
  4758.4    0.07       0  4851.7    0.16       0  4988.6    0.07       0
  4992.9    0.16       0
Bank Sta=4988.6,4992.9
Exp/Cntr=0.3,0.1

Type RM Length L Ch R = 1,3323,129,129,129
BEGIN DESCRIPTION:
Elm 79 3322.511
END DESCRIPTION:
XS GIS Cut Line= 3
      1534504.99      6768138.00      1534771.47      6768154.75
      1534955.01      6768138.00
#Sta/Elev= 30
  4733.0 2074.32  4743.0 2072.86  4753.0 2067.07  4763.1 2066.86  4773.1 2063.40
  4793.1 2058.37  4802.5 2056.82  4815.4 2055.07  4833.2 2055.43  4853.2 2054.05
  4873.3 2050.16  4883.3 2047.41  4933.4 2038.31  4993.5 2037.36  5004.3 2037.78
  5013.6 2036.86  5016.8 2034.24  5017.1 2033.74  5020.8 2033.74  5021.1 2034.24
  5024.0 2035.40  5033.7 2036.47  5063.8 2037.43  5083.9 2040.06  5093.9 2046.03
  5114.0 2054.36  5129.2 2066.79  5134.2 2065.17  5164.2 2074.29  5184.3 2077.15
#Mann=4,-1,0
  4733.0    0.07       0  4802.5    0.16       0  5016.8    0.07       0
  5021.1    0.16       0
Bank Sta=5016.8,5021.1
Exp/Cntr=0.3,0.1

Type RM Length L Ch R = 1,3194,110,110,110
BEGIN DESCRIPTION:
Elm 79 3193.96
END DESCRIPTION:
XS GIS Cut Line= 3
      1534521.35      6768174.63      1534852.97      6768251.03
      1535078.17      6768212.92
#Sta/Elev= 30
  4658.2 2069.49  4672.2 2067.79  4691.5 2060.98  4696.7 2060.40  4701.8 2058.68
  4733.8 2052.15  4764.6 2052.92  4774.8 2051.20  4782.3 2048.25  4787.4 2047.94
  4805.6 2041.94  4836.4 2036.93  4963.7 2036.54  4977.9 2033.22  4978.2 2032.72
  4982.2 2033.22  4990.3 2034.63  4997.0 2037.90  5002.1 2037.90  5020.8 2045.04
  5041.1 2050.85  5051.5 2055.83  5101.7 2060.94  5112.1 2064.80  5132.4 2067.71
  5162.1 2067.73  5167.2 2071.17  5203.4 2072.42  5222.5 2072.03  5226.9 2075.21
#Mann=4,-1,0
  4658.2    0.07       0  4701.8    0.16       0  4977.9    0.07       0
  4982.2    0.16       0
Bank Sta=4977.9,4982.2
Exp/Cntr=0.3,0.1

Type RM Length L Ch R = 1,3084,169,169,169
BEGIN DESCRIPTION:
Elm 79 3083.79
END DESCRIPTION:
XS GIS Cut Line= 3
      1534517.94      6768176.40      1534809.56      6768346.51
      1535200.08      6768339.57
#Sta/Elev= 30
  4664.7 2070.23  4678.2 2069.39  4684.5 2066.30  4713.1 2058.34  4752.7 2049.50
  4758.4 2049.00  4774.2 2050.86  4788.6 2049.43  4823.4 2040.63  4838.7 2038.83
  4846.5 2036.64  4993.3 2035.65  5002.3 2034.33  5005.6 2030.62  5005.9 2030.12
  5009.9 2030.62  5017.8 2033.89  5027.8 2035.26  5077.8 2038.45  5097.8 2043.16
  5117.8 2043.96  5157.8 2051.87  5196.3 2066.98  5201.3 2065.03  5207.8 2068.07
  5227.8 2071.57  5317.8 2074.66  5347.8 2076.64  5367.8 2076.22  5392.9 2073.87
#Mann=4,-1,0
  4664.7    0.07       0  4713.1    0.16       0  5005.6    0.07       0
  5009.9    0.16       0
Bank Sta=5005.6,5009.9
Exp/Cntr=0.3,0.1

Type RM Length L Ch R = 1,2915,90,90,90
BEGIN DESCRIPTION:
Elm 79 2915.44
END DESCRIPTION:
XS GIS Cut Line= 3
      1534509.22      6768186.79      1534811.30      6768520.12
      1535081.03      6768596.20
#Sta/Elev= 30
  4559.2 2074.22  4564.0 2069.73  4585.6 2067.83  4592.4 2064.25  4606.5 2060.13
  4622.2 2057.34  4641.8 2051.05  4663.3 2048.38  4670.1 2046.11  4748.5 2040.09
  4769.4 2037.10  4812.0 2034.73  4960.7 2033.15  4967.4 2031.00  4974.9 2032.28
  4981.6 2028.00  4986.9 2027.17  4987.2 2026.67  4991.2 2027.17  4995.8 2031.96
  5064.8 2032.91  5097.3 2037.53  5165.3 2065.85  5199.3 2074.76  5204.5 2072.27
  5231.1 2074.46  5256.3 2067.03  5262.3 2066.04  5272.5 2067.41  5289.3 2073.62
#Mann=5,-1,0
  4559.2    0.07       0  4622.2    0.16       0  4986.9    0.07       0
  4991.2    0.16       0  5256.3    0.07       0
Bank Sta=4986.9,4991.2
Exp/Cntr=0.3,0.1

Type RM Length L Ch R = 1,2825,158,158,158
BEGIN DESCRIPTION:
Elm 79 2824.903
END DESCRIPTION:
XS GIS Cut Line= 3
      1534454.99      6768187.98      1534756.35      6768586.21
      1535054.99      6768737.99
#Sta/Elev= 30
  4500.6 2076.50  4514.2 2077.96  4537.0 2076.30  4587.0 2067.94  4614.0 2060.29
  4635.0 2056.83  4678.5 2046.71  4713.9 2041.68  4751.3 2041.12  4807.5 2036.30
  4822.1 2036.96  4828.4 2034.64  4836.6 2036.29  4878.3 2032.87  4951.1 2030.79
  5002.0 2031.43  5018.7 2027.95  5019.0 2027.45  5023.1 2027.95  5031.8 2031.87
  5104.2 2032.05  5155.5 2040.08  5187.6 2043.13  5209.8 2053.04  5222.8 2061.33
  5232.1 2064.20  5254.3 2075.18  5267.7 2078.49  5282.2 2079.50  5335.0 2087.02
#Mann=5,-1,0
  4500.6    0.07       0  4635.0    0.16       0  5018.7    0.07       0
  5023.1    0.16       0  5282.2    0.07       0
Bank Sta=5018.7,5023.1
Exp/Cntr=0.3,0.1

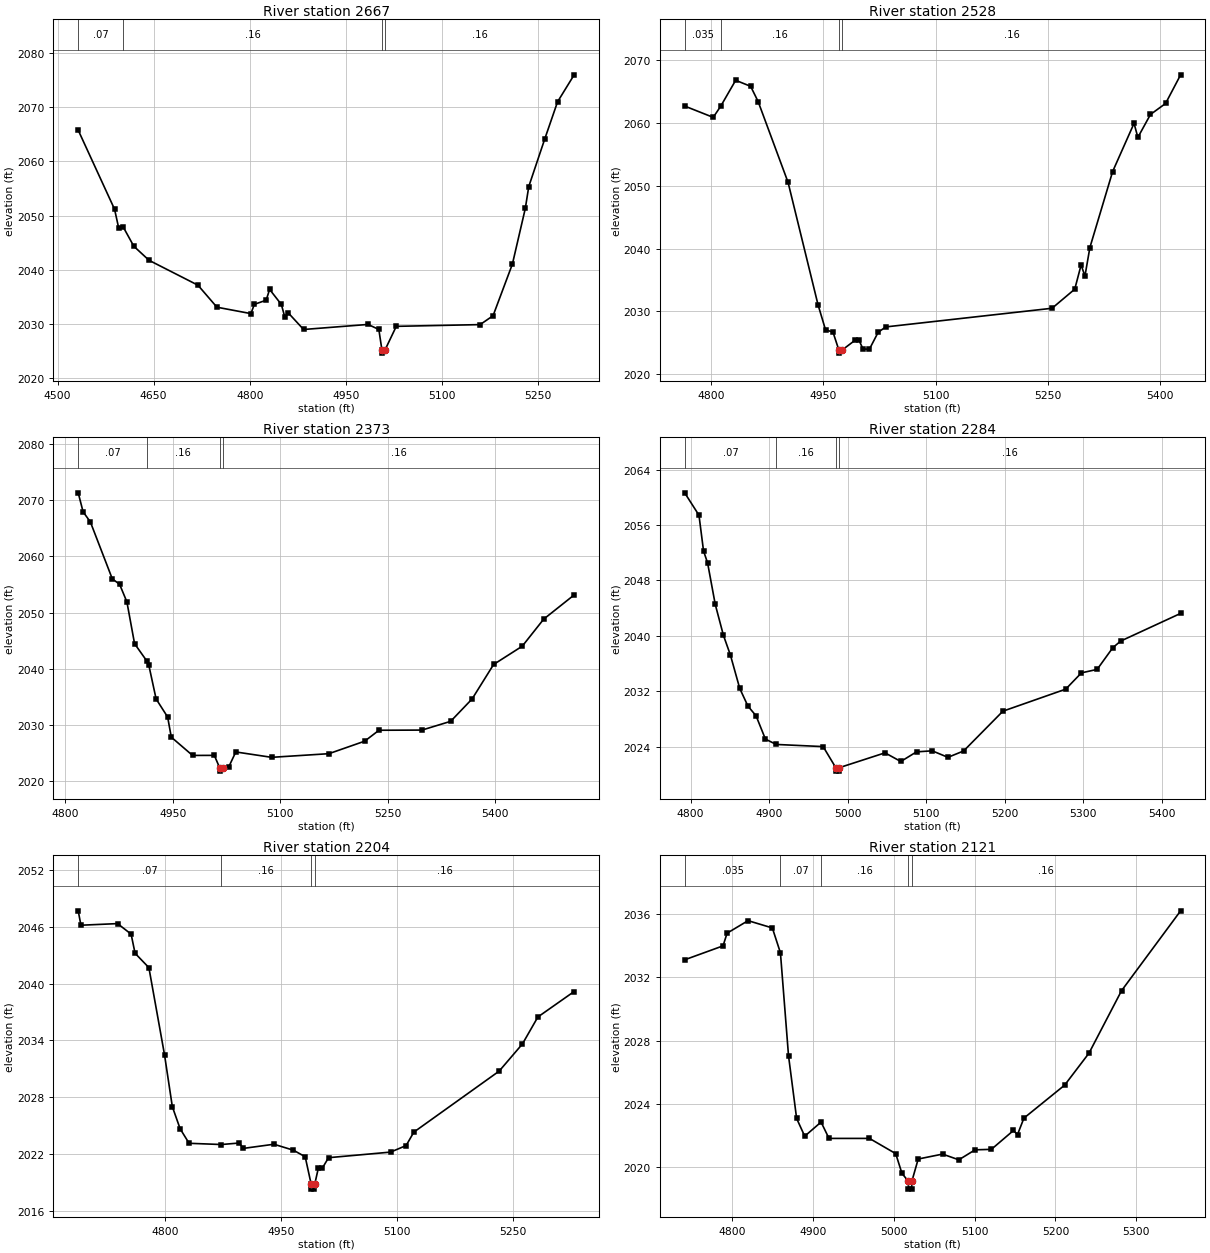
Type RM Length L Ch R = 1,2667,139,139,139
BEGIN DESCRIPTION:
Elm 79 2666.91
END DESCRIPTION:
XS GIS Cut Line= 3
      1534495.32      6768285.73      1534675.88      6768716.30
      1534980.72      6768750.95
#Sta/Elev= 30
  4532.3 2065.75  4589.0 2051.17  4595.3 2047.78  4602.2 2047.96  4619.0 2044.35
  4642.8 2041.75  4719.1 2037.16  4748.7 2033.10  4801.7 2031.92  4807.1 2033.63
  4825.5 2034.39  4830.9 2036.38  4849.2 2033.61  4854.7 2031.24  4860.1 2032.04
  4883.9 2028.99  4984.4 2029.92  5001.3 2029.00  5006.2 2025.13  5006.5 2024.63
  5010.6 2025.13  5028.5 2029.57  5159.3 2029.89  5179.5 2031.53  5209.7 2041.07
  5229.8 2051.32  5235.2 2055.36  5260.0 2064.08  5280.1 2070.98  5306.0 2075.96
#Mann=4,-1,0
  4532.3    0.07       0  4602.2    0.16       0  5006.2    0.07       0
  5010.6    0.16       0
Bank Sta=5006.2,5010.6
Exp/Cntr=0.3,0.1

Type RM Length L Ch R = 1,2528,155,155,155
BEGIN DESCRIPTION:
Elm 79 2527.57
END DESCRIPTION:
XS GIS Cut Line= 3
      1534326.88      6768777.07      1534559.56      6768780.54
      1534984.93      6768841.31
#Sta/Elev= 30
  4764.9 2062.69  4803.0 2060.89  4812.9 2062.64  4833.0 2066.79  4853.0 2065.83
  4863.0 2063.41  4903.0 2050.54  4943.0 2031.07  4953.0 2027.09  4963.0 2026.71
  4970.8 2023.87  4971.1 2023.37  4975.3 2023.87  4992.8 2025.45  4997.6 2025.45
  5003.1 2024.03  5011.6 2023.99  5023.3 2026.68  5033.4 2027.54  5255.6 2030.51
  5285.9 2033.55  5294.4 2037.41  5299.5 2035.62  5306.1 2040.17  5336.5 2052.27
  5365.1 2059.94  5370.2 2057.70  5387.0 2061.35  5407.2 2063.10  5427.3 2067.66
#Mann=4,-1,0
  4764.9   0.035       0  4812.9    0.16       0  4970.8    0.07       0
  4975.3    0.16       0
Bank Sta=4970.8,4975.3
Exp/Cntr=0.3,0.1

Type RM Length L Ch R = 1,2373,89,89,89
BEGIN DESCRIPTION:
Elm 79 2372.873
END DESCRIPTION:
XS GIS Cut Line= 3
      1534278.30      6768858.66      1534456.96      6768893.89
      1534967.54      6768898.60
#Sta/Elev= 30
  4817.9 2071.35  4824.7 2067.97  4834.9 2066.15  4865.5 2056.01  4875.7 2055.04
  4885.9 2051.90  4896.6 2044.45  4913.4 2041.42  4916.5 2040.63  4926.7 2034.59
  4942.8 2031.37  4947.9 2027.78  4977.6 2024.52  5008.0 2024.53  5015.8 2022.22
  5016.1 2021.72  5020.3 2022.22  5028.0 2022.43  5038.0 2025.14  5088.0 2024.18
  5168.0 2024.83  5218.0 2027.06  5238.0 2029.01  5298.0 2029.04  5338.1 2030.60
  5368.1 2034.60  5398.1 2040.74  5438.1 2044.00  5468.1 2048.83  5510.6 2053.14
#Mann=4,-1,0
  4817.9    0.07       0  4913.4    0.16       0  5015.8    0.07       0
  5020.3    0.16       0
Bank Sta=5015.8,5020.3
Exp/Cntr=0.3,0.1

Type RM Length L Ch R = 1,2284,80,80,80
BEGIN DESCRIPTION:
Elm 79 3965
END DESCRIPTION:
XS GIS Cut Line= 3
      1534257.48      6768926.37      1534457.36      6768982.10
      1534881.27      6768973.27
#Sta/Elev= 30
  4792.5 2060.64  4810.7 2057.41  4816.5 2052.26  4821.7 2050.51  4831.4 2044.55
  4841.8 2040.09  4850.7 2037.24  4862.6 2032.42  4873.0 2029.87  4883.4 2028.46
  4895.3 2025.10  4909.1 2024.33  4968.8 2024.02  4984.9 2020.98  4985.2 2020.48
  4989.1 2020.48  4989.4 2020.98  5047.6 2023.12  5067.7 2021.87  5087.7 2023.26
  5107.7 2023.41  5127.7 2022.47  5147.7 2023.39  5197.7 2029.13  5277.7 2032.31
  5297.7 2034.66  5317.7 2035.16  5337.7 2038.30  5347.7 2039.25  5424.0 2043.24
#Mann=4,-1,0
  4792.5    0.07       0  4909.1    0.16       0  4984.9    0.07       0
  4989.4    0.16       0
Bank Sta=4984.9,4989.4
Exp/Cntr=0.3,0.1

Type RM Length L Ch R = 1,2204,83,83,83
BEGIN DESCRIPTION:
Elm 79 3963
END DESCRIPTION:
XS GIS Cut Line= 3
      1534184.60      6769002.77      1534493.52      6769047.90
      1534821.73      6769023.72
#Sta/Elev= 30
  4687.8 2047.68  4691.3 2046.16  4738.7 2046.33  4756.2 2045.22  4761.3 2043.20
  4779.2 2041.68  4799.4 2032.48  4809.5 2027.00  4819.6 2024.66  4831.2 2023.13
  4872.9 2023.00  4896.1 2023.16  4901.2 2022.59  4940.9 2023.03  4966.1 2022.40
  4981.3 2021.71  4989.1 2018.79  4989.4 2018.29  4993.3 2018.29  4993.6 2018.79
  4998.2 2020.47  5003.2 2020.47  5011.5 2021.61  5091.7 2022.20  5111.8 2022.89
  5121.8 2024.31  5232.1 2030.75  5262.2 2033.62  5282.2 2036.47  5329.1 2039.16
#Mann=4,-1,0
  4687.8    0.07       0  4872.9    0.16       0  4989.1    0.07       0
  4993.6    0.16       0
Bank Sta=4989.1,4993.6
Exp/Cntr=0.3,0.1

Type RM Length L Ch R = 1,2121,72,72,72
BEGIN DESCRIPTION:
Elm 79 3962
END DESCRIPTION:
XS GIS Cut Line= 3
      1534196.73      6769124.29      1534454.75      6769117.84
      1534807.62      6769082.82
#Sta/Elev= 30
  4741.9 2033.10  4789.3 2033.98  4794.3 2034.78  4820.2 2035.57  4850.2 2035.11
  4860.2 2033.54  4870.2 2027.04  4880.2 2023.09  4890.2 2021.97  4910.4 2022.86
  4920.2 2021.83  4970.2 2021.83  5002.6 2020.87  5010.3 2019.63  5018.1 2019.13
  5018.4 2018.63  5022.3 2018.63  5022.6 2019.13  5030.4 2020.53  5060.5 2020.84
  5080.6 2020.48  5100.7 2021.11  5120.8 2021.14  5148.1 2022.33  5153.1 2022.07
  5161.0 2023.11  5211.3 2025.19  5241.4 2027.21  5281.6 2031.15  5354.6 2036.19
#Mann=5,-1,0
  4741.9   0.035       0  4860.2    0.07       0  4910.4    0.16       0
  5018.1    0.07       0  5022.6    0.16       0
Bank Sta=5018.1,5022.6
Exp/Cntr=0.3,0.1