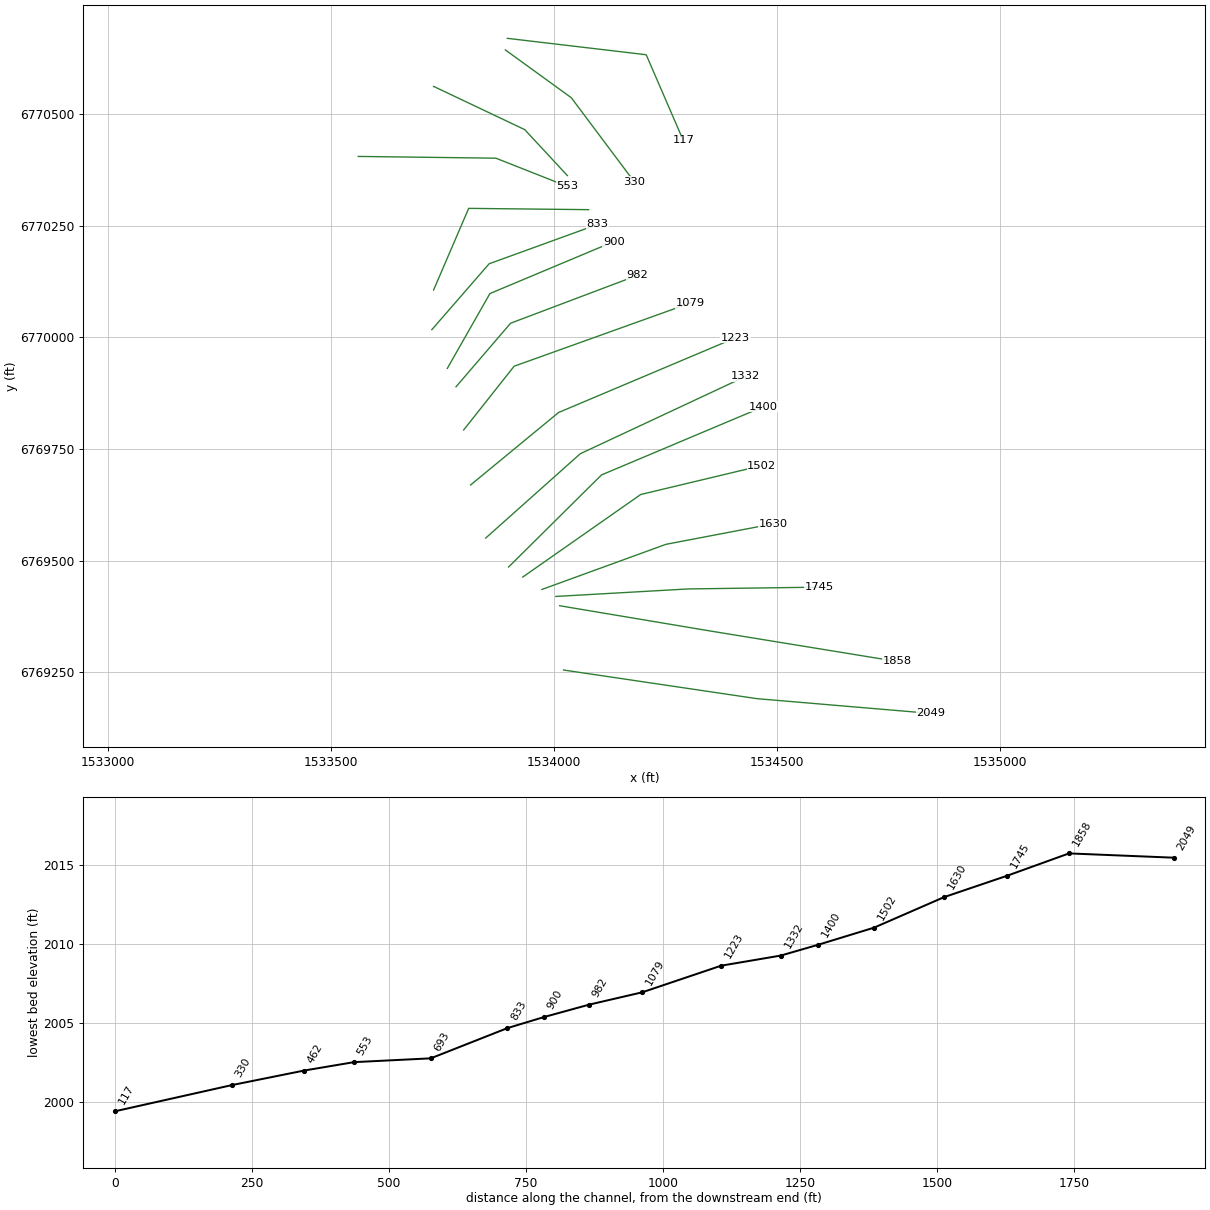
HEC-RAS study Elm 79.prj: Elm 79 Base Level Engineering

--- Elm 79.g01 (geometry) --- (continued)

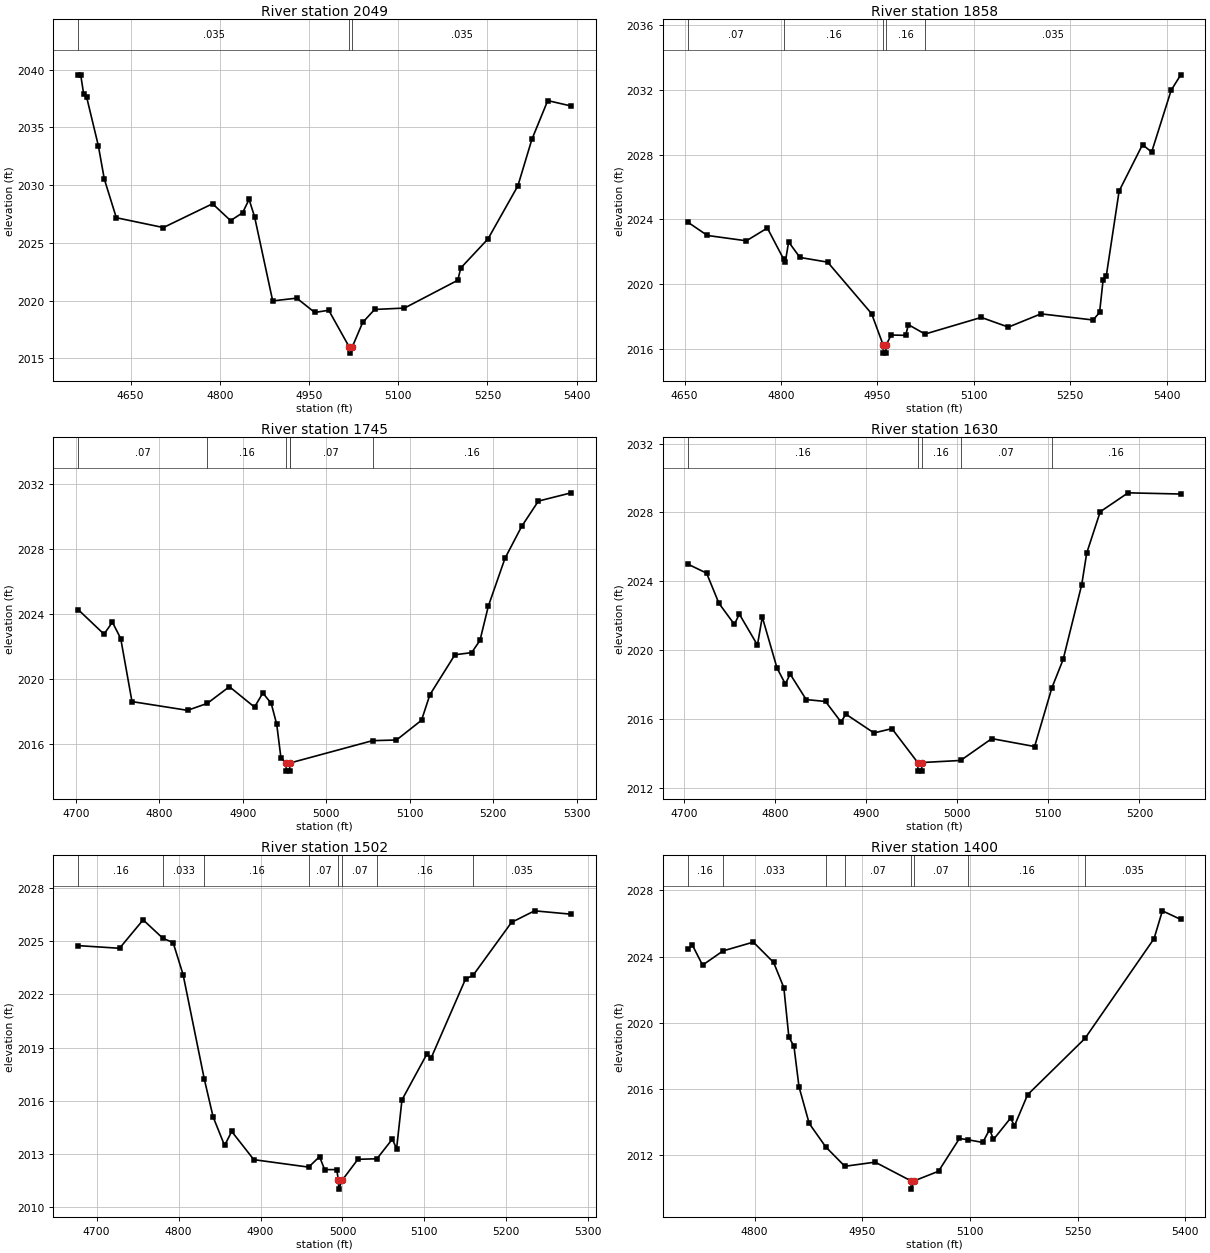
Type RM Length L Ch R = 1,2049,191,191,191
BEGIN DESCRIPTION:
Elm 79 3961
END DESCRIPTION:
XS GIS Cut Line= 3
      1534021.38      6769254.50      1534454.95      6769190.26
      1534844.25      6769157.28
#Sta/Elev= 30
  4561.7 2039.54  4566.1 2039.54  4571.2 2037.85  4576.2 2037.59  4595.7 2033.42
  4605.8 2030.52  4626.0 2027.17  4705.1 2026.32  4787.8 2028.38  4818.1 2026.92
  4838.3 2027.60  4849.2 2028.76  4858.5 2027.24  4888.9 2019.97  4929.3 2020.21
  4959.6 2018.97  4983.1 2019.16  5017.9 2015.95  5018.2 2015.45  5022.4 2015.95
  5040.2 2018.11  5060.3 2019.23  5110.4 2019.35  5200.1 2021.76  5205.1 2022.82
  5250.9 2025.34  5301.1 2029.93  5324.6 2033.95  5351.3 2037.31  5390.7 2036.84
#Mann=3,-1,0
  4561.7   0.035       0  5017.9   0.035       0  5022.4   0.035       0
Bank Sta=5017.9,5022.4
Exp/Cntr=0.3,0.1

Type RM Length L Ch R = 1,1858,113,113,113
BEGIN DESCRIPTION:
Elm 79 3958
END DESCRIPTION:
XS GIS Cut Line= 3
      1534012.72      6769398.59      1534353.07      6769341.51
      1534769.67      6769273.59
#Sta/Elev= 30
  4654.9 2023.83  4685.6 2023.00  4746.3 2022.67  4778.9 2023.46  4804.3 2021.53
  4806.9 2021.37  4812.0 2022.60  4829.6 2021.64  4872.7 2021.35  4941.1 2018.16
  4959.1 2016.22  4959.4 2015.72  4963.3 2015.72  4963.7 2016.22  4971.5 2016.84
  4994.0 2016.82  4998.4 2017.48  5024.2 2016.90  5111.7 2017.93  5153.9 2017.33
  5204.6 2018.15  5285.7 2017.77  5295.8 2018.24  5301.2 2020.22  5306.2 2020.49
  5326.2 2025.75  5362.6 2028.62  5376.8 2028.16  5407.2 2031.99  5422.1 2032.94
#Mann=5,-1,0
  4654.9    0.07       0  4804.3    0.16       0  4959.1    0.07       0
  4963.7    0.16       0  5024.2   0.035       0
Bank Sta=4959.1,4963.7
Exp/Cntr=0.3,0.1

Type RM Length L Ch R = 1,1745,115,115,115
BEGIN DESCRIPTION:
Elm 79 3960
END DESCRIPTION:
XS GIS Cut Line= 3
      1534003.99      6769419.43      1534300.81      6769436.26
      1534594.28      6769440.26
#Sta/Elev= 30
  4702.7 2024.28  4733.8 2022.76  4743.8 2023.50  4753.8 2022.49  4767.3 2018.60
  4833.9 2018.06  4857.5 2018.49  4884.0 2019.52  4914.1 2018.26  4924.1 2019.13
  4934.1 2018.49  4940.7 2017.20  4945.7 2015.15  4951.8 2014.81  4952.2 2014.31
  4956.1 2014.31  4956.4 2014.81  4956.5 2014.81  5055.5 2016.19  5084.2 2016.23
  5114.2 2017.45  5124.2 2019.02  5154.2 2021.49  5174.2 2021.62  5184.2 2022.37
  5194.2 2024.48  5214.2 2027.44  5234.2 2029.41  5254.2 2030.97  5293.5 2031.48
#Mann=6,-1,0
  4702.7    0.07       0  4857.5    0.16       0  4951.8    0.07       0
  4956.4    0.16       0  4956.5    0.07       0  5055.5    0.16       0
Bank Sta=4951.8,4956.4
Exp/Cntr=0.3,0.1

Type RM Length L Ch R = 1,1630,128,128,128
BEGIN DESCRIPTION:
Elm 79 3959
END DESCRIPTION:
XS GIS Cut Line= 3
      1533972.79      6769435.07      1534250.84      6769536.28
      1534491.79      6769582.28
#Sta/Elev= 30
  4704.1 2025.00  4724.9 2024.47  4738.4 2022.72  4755.4 2021.49  4760.8 2022.09
  4780.7 2020.29  4786.0 2021.92  4802.2 2018.95  4811.3 2018.03  4816.6 2018.60
  4834.2 2017.12  4855.4 2017.01  4872.4 2015.82  4877.8 2016.27  4908.6 2015.18
  4928.3 2015.43  4956.6 2013.46  4956.9 2012.96  4960.8 2012.96  4961.2 2013.46
  5003.7 2013.58  5037.9 2014.85  5084.9 2014.39  5103.9 2017.81  5116.2 2019.45
  5136.6 2023.80  5142.1 2025.64  5156.9 2028.04  5187.5 2029.14  5245.3 2029.07
#Mann=5,-1,0
  4704.1    0.16       0  4956.6    0.07       0  4961.2    0.16       0
  5003.7    0.07       0  5103.9    0.16       0
Bank Sta=4956.6,4961.2
Exp/Cntr=0.3,0.1

Type RM Length L Ch R = 1,1502,102,102,102
BEGIN DESCRIPTION:
Elm 79 3957
END DESCRIPTION:
XS GIS Cut Line= 3
      1533929.97      6769462.98      1534194.37      6769648.00
      1534465.83      6769712.84
#Sta/Elev= 30
  4677.3 2024.75  4727.9 2024.60  4756.7 2026.20  4780.9 2025.16  4793.3 2024.92
  4805.5 2023.11  4831.3 2017.24  4842.1 2015.10  4856.1 2013.49  4864.8 2014.28
  4891.8 2012.69  4958.7 2012.27  4972.0 2012.86  4978.2 2012.13  4993.0 2012.13
  4995.0 2011.53  4995.4 2011.03  4999.6 2011.53  5018.8 2012.71  5042.0 2012.74
  5060.9 2013.85  5066.0 2013.30  5072.6 2016.06  5103.0 2018.64  5108.1 2018.41
  5150.2 2022.87  5159.3 2023.07  5206.3 2026.06  5234.4 2026.71  5279.1 2026.52
#Mann=8,-1,0
  4677.3    0.16       0  4780.9   0.033       0  4831.3    0.16       0
  4958.7    0.07       0  4995.0    0.07       0  4999.6    0.07       0
  5042.0    0.16       0  5159.3   0.035       0
Bank Sta=4995,4999.6
Exp/Cntr=0.3,0.1

Type RM Length L Ch R = 1,1400,68,68,68
BEGIN DESCRIPTION:
Elm 79 3955
END DESCRIPTION:
XS GIS Cut Line= 3
      1533898.14      6769485.44      1534106.46      6769691.90
      1534469.27      6769844.77
#Sta/Elev= 30
  4706.7 2024.44  4713.4 2024.68  4727.5 2023.48  4756.0 2024.34  4798.2 2024.87
  4826.5 2023.64  4840.7 2022.12  4847.7 2019.14  4854.8 2018.58  4861.8 2016.14
  4876.0 2013.92  4899.1 2012.50  4925.7 2011.33  4967.9 2011.58  5017.8 2010.45
  5018.2 2009.95  5022.4 2010.45  5056.2 2011.03  5085.4 2013.01  5097.5 2012.93
  5117.8 2012.77  5127.4 2013.55  5132.8 2012.95  5156.6 2014.24  5162.0 2013.77
  5180.3 2015.65  5260.2 2019.05  5356.5 2025.08  5368.1 2026.76  5393.7 2026.24
#Mann=8,-1,0
  4706.7    0.16       0  4756.0   0.033       0  4899.1    0.16       0
  4925.7    0.07       0  5017.8    0.07       0  5022.4    0.07       0
  5097.5    0.16       0  5260.2   0.035       0
Bank Sta=5017.8,5022.4
Exp/Cntr=0.3,0.1

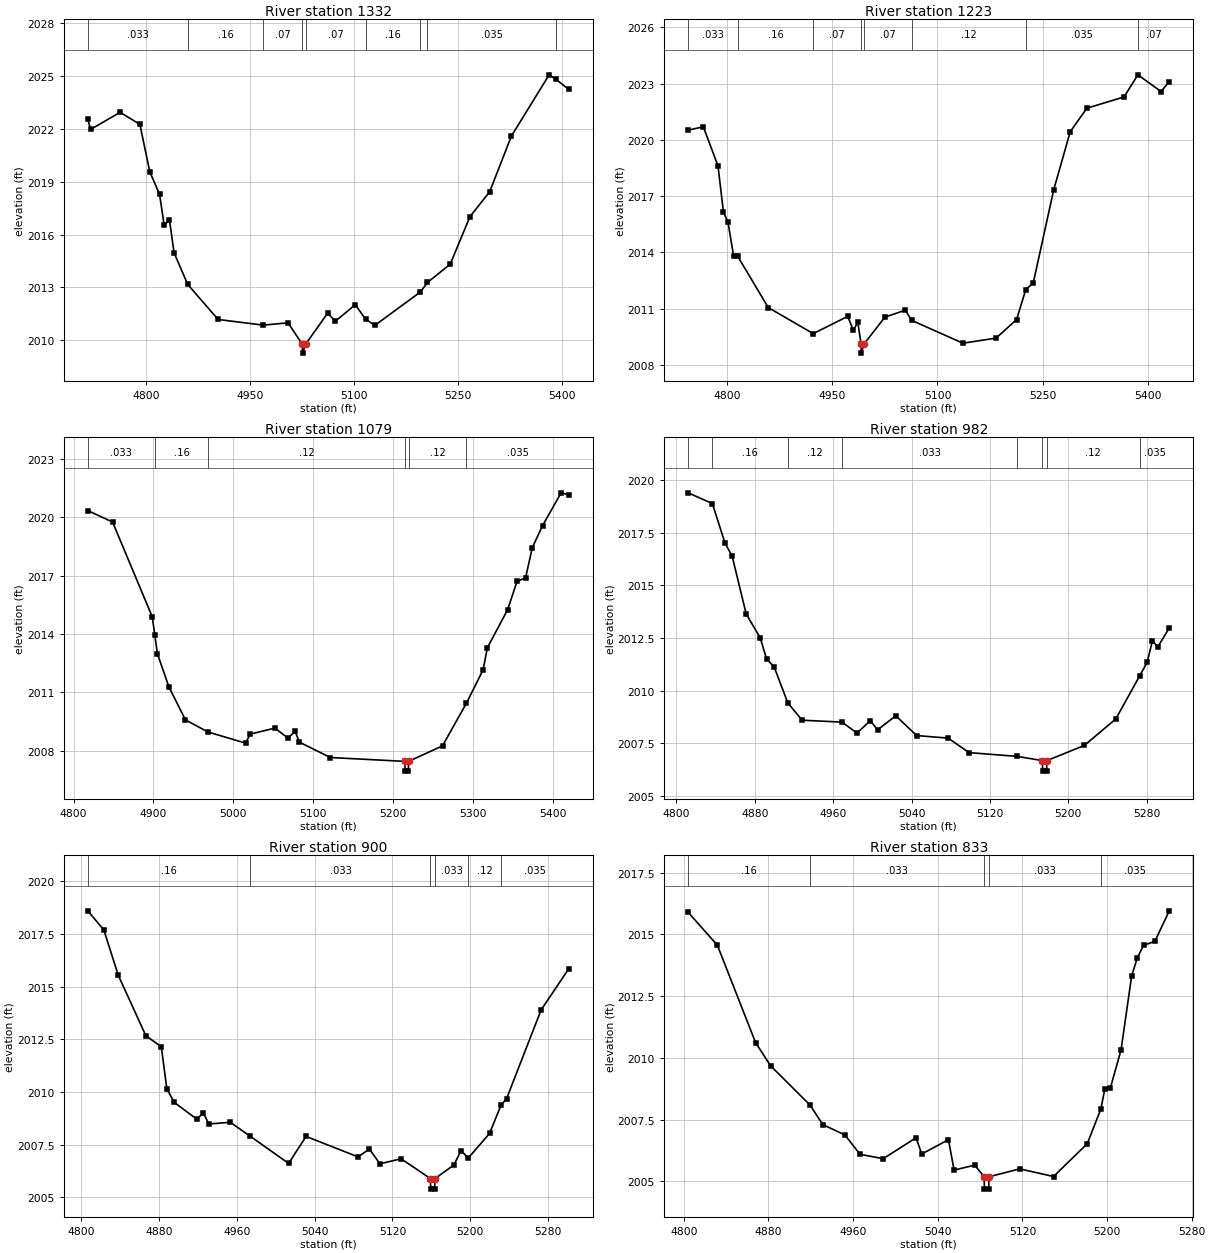
Type RM Length L Ch R = 1,1332,109,109,109
BEGIN DESCRIPTION:
Elm 79 3954
END DESCRIPTION:
XS GIS Cut Line= 3
      1533846.85      6769550.35      1534058.89      6769739.43
      1534430.01      6769913.00
#Sta/Elev= 30
  4715.9 2022.58  4720.0 2021.97  4762.6 2022.94  4791.1 2022.26  4805.3 2019.58
  4819.5 2018.28  4826.2 2016.52  4833.7 2016.85  4840.4 2014.97  4860.1 2013.17
  4903.9 2011.18  4969.1 2010.86  5004.8 2010.99  5025.4 2009.77  5025.7 2009.27
  5030.0 2009.77  5061.9 2011.54  5073.0 2011.08  5101.7 2012.02  5116.5 2011.20
  5130.1 2010.85  5195.6 2012.74  5205.8 2013.28  5238.6 2014.32  5267.1 2017.02
  5295.5 2018.43  5326.9 2021.60  5381.3 2025.07  5391.1 2024.81  5409.7 2024.24
#Mann=9,-1,0
  4715.9   0.033       0  4860.1    0.16       0  4969.1    0.07       0
  5025.4    0.07       0  5030.0    0.07       0  5116.5    0.16       0
  5195.6    0.12       0  5205.8   0.035       0  5391.1    0.07       0
Bank Sta=5025.4,5030
Exp/Cntr=0.3,0.1

Type RM Length L Ch R = 1,1223,144,144,144
BEGIN DESCRIPTION:
Elm 79 3953
END DESCRIPTION:
XS GIS Cut Line= 3
      1533813.05      6769669.44      1534010.17      6769831.84
      1534406.77      6769999.29
#Sta/Elev= 30
  4744.6 2020.52  4766.2 2020.70  4787.1 2018.62  4794.9 2016.15  4801.4 2015.61
  4809.3 2013.83  4815.1 2013.80  4858.8 2011.06  4922.9 2009.67  4972.1 2010.59
  4980.0 2009.85  4986.5 2010.27  4991.0 2009.13  4991.3 2008.63  4995.6 2009.13
  5025.1 2010.55  5054.2 2010.92  5063.1 2010.38  5136.2 2009.16  5183.6 2009.43
  5212.8 2010.42  5225.9 2012.02  5236.5 2012.36  5265.8 2017.35  5289.3 2020.44
  5313.0 2021.69  5365.9 2022.29  5385.8 2023.47  5418.7 2022.58  5430.5 2023.11
#Mann=8,-1,0
  4744.6   0.033       0  4815.1    0.16       0  4922.9    0.07       0
  4991.0    0.07       0  4995.6    0.07       0  5063.1    0.12       0
  5225.9   0.035       0  5385.8    0.07       0
Bank Sta=4991,4995.6
Exp/Cntr=0.3,0.1

Type RM Length L Ch R = 1,1079,97,97,97
BEGIN DESCRIPTION:
Elm 79 3952
END DESCRIPTION:
XS GIS Cut Line= 3
      1533797.43      6769792.72      1533910.52      6769935.57
      1534306.06      6770077.40
#Sta/Elev= 30
  4817.8 2020.34  4848.9 2019.75  4898.6 2014.88  4901.8 2013.94  4905.0 2012.99
  4919.4 2011.28  4940.2 2009.58  4968.4 2008.96  5015.4 2008.39  5021.3 2008.85
  5052.1 2009.16  5068.5 2008.65  5077.5 2008.99  5082.8 2008.44  5121.6 2007.65
  5214.9 2007.45  5215.2 2006.95  5219.2 2006.95  5219.5 2007.45  5262.0 2008.25
  5291.8 2010.43  5312.8 2012.15  5318.2 2013.29  5343.6 2015.25  5355.3 2016.70
  5366.0 2016.88  5374.4 2018.43  5387.2 2019.56  5410.5 2021.25  5420.2 2021.15
#Mann=6,-1,0
  4817.8   0.033       0  4901.8    0.16       0  4968.4    0.12       0
  5214.9    0.07       0  5219.5    0.12       0  5291.8   0.035       0
Bank Sta=5214.9,5219.5
Exp/Cntr=0.3,0.1

Type RM Length L Ch R = 1,982,82,82,82
BEGIN DESCRIPTION:
Elm 79 3951
END DESCRIPTION:
XS GIS Cut Line= 3
      1533780.24      6769889.46      1533902.64      6770032.02
      1534186.11      6770139.06
#Sta/Elev= 30
  4812.1 2019.40  4836.8 2018.89  4849.7 2017.01  4857.0 2016.39  4871.3 2013.64
  4885.6 2012.51  4892.2 2011.49  4899.8 2011.13  4913.8 2009.41  4928.4 2008.59
  4969.0 2008.50  4984.4 2007.98  4998.0 2008.57  5005.3 2008.13  5023.9 2008.80
  5045.3 2007.86  5077.3 2007.74  5098.7 2007.05  5148.0 2006.87  5173.5 2006.67
  5173.8 2006.17  5177.8 2006.17  5178.1 2006.67  5216.3 2007.39  5248.4 2008.65
  5272.9 2010.71  5280.4 2011.34  5285.8 2012.37  5291.2 2012.07  5303.0 2012.98
#Mann=8,-1,0
  4812.1   0.033       0  4836.8    0.16       0  4913.8    0.12       0
  4969.0   0.033       0  5148.0    0.12       0  5173.5   0.033       0
  5178.1    0.12       0  5272.9   0.035       0
Bank Sta=5173.5,5178.1
Exp/Cntr=0.3,0.1

Type RM Length L Ch R = 1,900,67,67,67
BEGIN DESCRIPTION:
Elm 79 3950
END DESCRIPTION:
XS GIS Cut Line= 3
      1533760.72      6769930.68      1533856.23      6770098.51
      1534133.99      6770215.00
#Sta/Elev= 30
  4806.9 2018.59  4823.4 2017.69  4838.3 2015.53  4866.6 2012.67  4882.5 2012.14
  4888.2 2010.14  4895.9 2009.50  4918.9 2008.71  4925.7 2009.00  4931.4 2008.48
  4953.4 2008.56  4974.1 2007.89  5013.3 2006.61  5031.2 2007.89  5084.6 2006.92
  5096.3 2007.29  5107.1 2006.59  5128.8 2006.83  5159.0 2005.89  5159.3 2005.39
  5163.3 2005.39  5163.6 2005.89  5183.0 2006.53  5190.5 2007.22  5197.8 2006.86
  5219.7 2008.03  5231.5 2009.37  5237.2 2009.68  5272.7 2013.89  5301.2 2015.85
#Mann=6,-1,0
  4806.9    0.16       0  4974.1   0.033       0  5159.0   0.033       0
  5163.6   0.033       0  5197.8    0.12       0  5231.5   0.035       0
Bank Sta=5159,5163.6
Exp/Cntr=0.3,0.1

Type RM Length L Ch R = 1,833,140,140,140
BEGIN DESCRIPTION:
Elm 79 3949
END DESCRIPTION:
XS GIS Cut Line= 3
      1533725.99      6770017.49      1533854.55      6770165.31
      1534097.84      6770253.54
#Sta/Elev= 30
  4804.1 2015.89  4831.7 2014.56  4867.8 2010.62  4882.0 2009.68  4919.1 2008.10
  4931.4 2007.30  4952.3 2006.88  4966.5 2006.10  4988.4 2005.92  5019.5 2006.77
  5024.8 2006.11  5050.1 2006.69  5055.4 2005.46  5074.9 2005.66  5083.8 2005.19
  5084.1 2004.69  5088.1 2004.69  5088.4 2005.19  5117.5 2005.51  5149.4 2005.20
  5181.3 2006.53  5194.1 2007.93  5197.9 2008.75  5203.2 2008.80  5213.2 2010.32
  5223.2 2013.31  5228.5 2014.04  5234.5 2014.56  5245.1 2014.71  5258.8 2015.95
#Mann=5,-1,0
  4804.1    0.16       0  4919.1   0.033       0  5083.8   0.033       0
  5088.4   0.033       0  5194.1   0.035       0
Bank Sta=5083.8,5088.4
Exp/Cntr=0.3,0.1

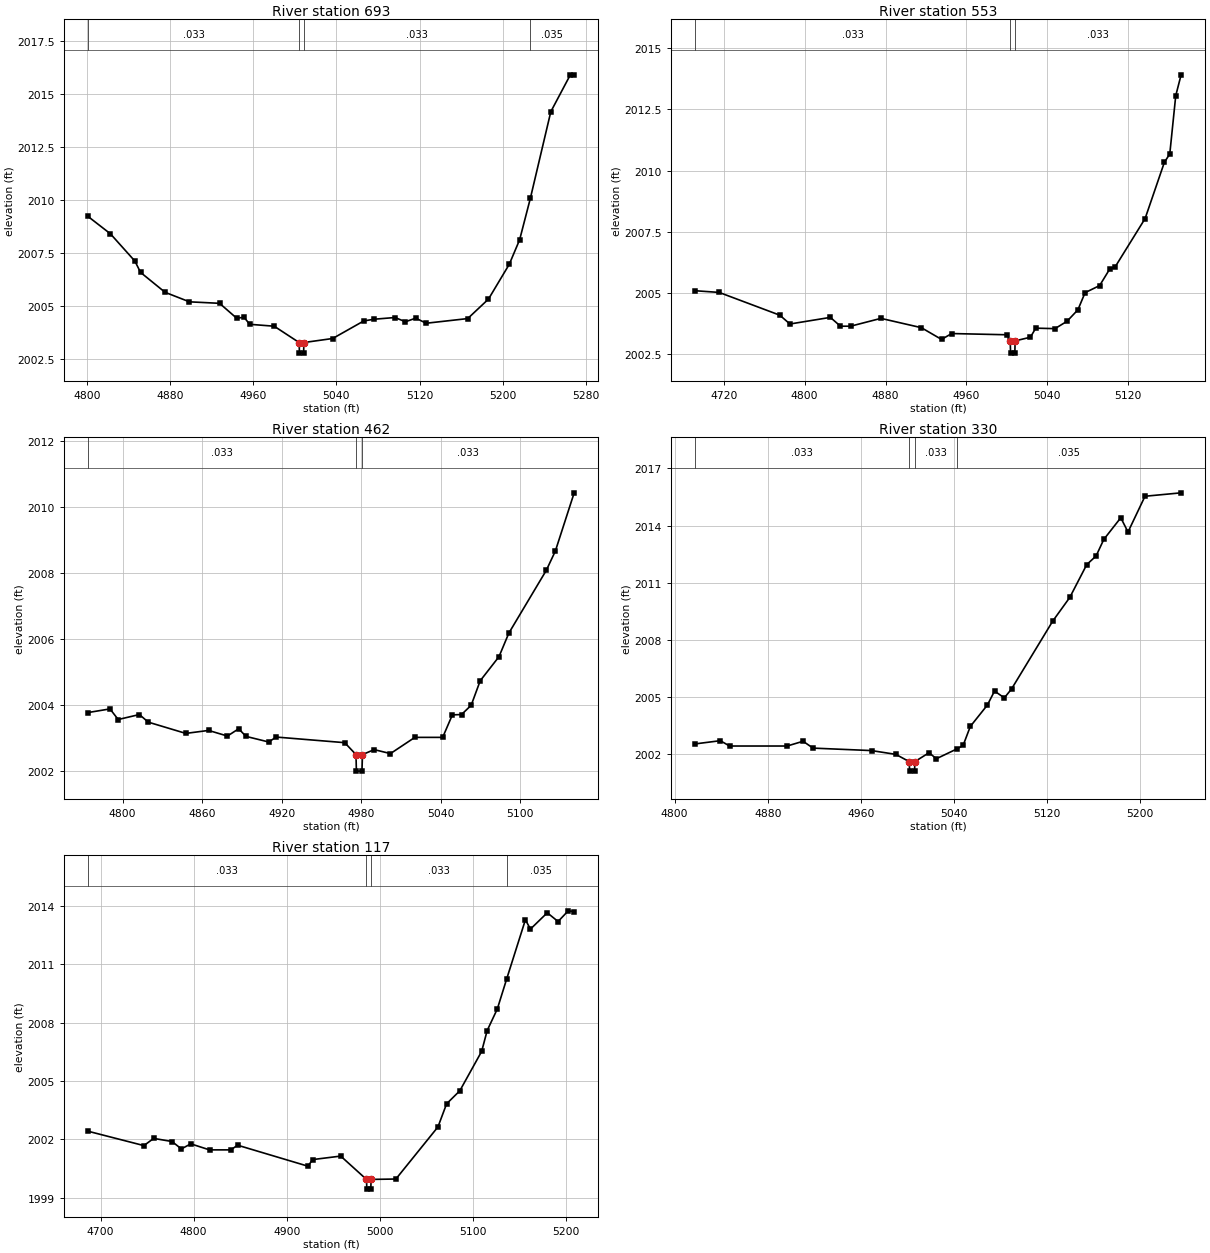
Type RM Length L Ch R = 1,693,140,140,140
BEGIN DESCRIPTION:
Elm 79 3948
END DESCRIPTION:
XS GIS Cut Line= 3
      1533730.00      6770106.49      1533808.65      6770289.51
      1534077.53      6770286.62
#Sta/Elev= 30
  4800.8 2009.23  4822.4 2008.41  4846.0 2007.12  4851.4 2006.59  4875.0 2005.65
  4898.5 2005.20  4927.5 2005.13  4943.9 2004.43  4951.1 2004.47  4956.5 2004.14
  4980.1 2004.05  5004.1 2003.28  5004.4 2002.78  5008.4 2002.78  5008.7 2003.28
  5036.4 2003.47  5066.4 2004.30  5076.4 2004.38  5096.4 2004.46  5106.4 2004.26
  5116.4 2004.43  5126.4 2004.19  5166.4 2004.41  5186.4 2005.33  5206.4 2006.97
  5216.4 2008.13  5226.8 2010.10  5246.4 2014.17  5265.2 2015.91  5268.9 2015.91
#Mann=4,-1,0
  4800.8   0.033       0  5004.1   0.033       0  5008.7   0.033       0
  5226.8   0.035       0
Bank Sta=5004.1,5008.7
Exp/Cntr=0.3,0.1

Type RM Length L Ch R = 1,553,91,91,91
BEGIN DESCRIPTION:
Elm 79 3947
END DESCRIPTION:
XS GIS Cut Line= 3
      1533561.05      6770405.97      1533869.62      6770402.04
      1534029.97      6770338.71
#Sta/Elev= 30
  4691.4 2005.09  4715.4 2005.02  4775.4 2004.09  4785.4 2003.73  4825.4 2004.00
  4835.4 2003.64  4845.4 2003.64  4875.4 2003.96  4915.4 2003.58  4935.4 2003.10
  4945.4 2003.34  5000.0 2003.29  5003.3 2003.04  5003.7 2002.54  5007.9 2002.54
  5008.2 2003.04  5023.3 2003.19  5028.6 2003.56  5047.6 2003.54  5059.5 2003.84
  5070.3 2004.31  5077.4 2005.01  5091.8 2005.30  5101.7 2005.97  5107.1 2006.06
  5136.8 2008.04  5155.8 2010.33  5161.2 2010.68  5167.1 2013.06  5172.4 2013.91
#Mann=3,-1,0
  4691.4   0.033       0  5003.3   0.033       0  5008.2   0.033       0
Bank Sta=5003.3,5008.2
Exp/Cntr=0.3,0.1

Type RM Length L Ch R = 1,462,132,132,132
BEGIN DESCRIPTION:
Elm 79 3946
END DESCRIPTION:
XS GIS Cut Line= 3
      1533729.98      6770563.01      1533934.25      6770466.08
      1534030.01      6770362.99
#Sta/Elev= 30
  4773.9 2003.78  4790.5 2003.89  4796.7 2003.57  4812.7 2003.72  4819.4 2003.49
  4847.7 2003.15  4864.9 2003.24  4879.1 2003.07  4887.6 2003.29  4893.1 2003.06
  4910.3 2002.89  4915.8 2003.04  4967.6 2002.87  4976.1 2002.51  4976.4 2002.01
  4980.6 2002.01  4981.0 2002.51  4989.8 2002.66  5002.1 2002.54  5020.5 2003.03
  5041.5 2003.03  5048.8 2003.71  5055.7 2003.72  5063.0 2004.00  5069.8 2004.74
  5084.0 2005.47  5091.4 2006.18  5119.7 2008.08  5126.5 2008.66  5140.7 2010.42
#Mann=3,-1,0
  4773.9   0.033       0  4976.1   0.033       0  4981.0   0.033       0
Bank Sta=4976.1,4981
Exp/Cntr=0.3,0.1

Type RM Length L Ch R = 1,330,213,213,213
BEGIN DESCRIPTION:
Elm 79 3945
END DESCRIPTION:
XS GIS Cut Line= 3
      1533890.90      6770644.72      1534038.68      6770537.63
      1534179.57      6770349.55
#Sta/Elev= 30
  4817.5 2002.52  4839.3 2002.69  4847.3 2002.41  4896.7 2002.41  4910.4 2002.66
  4918.9 2002.30  4969.2 2002.17  4990.1 2001.97  5001.5 2001.59  5001.9 2001.09
  5006.1 2001.09  5006.4 2001.59  5018.6 2002.06  5024.8 2001.74  5042.9 2002.27
  5047.8 2002.44  5054.0 2003.44  5068.6 2004.56  5074.8 2005.30  5083.2 2004.94
  5089.4 2005.41  5124.8 2008.98  5139.4 2010.22  5154.0 2011.95  5162.0 2012.40
  5168.6 2013.27  5183.2 2014.41  5189.4 2013.66  5204.0 2015.54  5235.0 2015.72
#Mann=4,-1,0
  4817.5   0.033       0  5001.5   0.033       0  5006.4   0.033       0
  5042.9   0.035       0
Bank Sta=5001.5,5006.4
Exp/Cntr=0.3,0.1

Type RM Length L Ch R = 1,117,0,0,0
BEGIN DESCRIPTION:
Elm 79 3944
END DESCRIPTION:
XS GIS Cut Line= 3
      1533895.31      6770670.73      1534206.64      6770633.97
      1534289.62      6770442.15
#Sta/Elev= 30
  4686.5 2002.42  4746.6 2001.68  4757.1 2002.05  4776.8 2001.89  4786.9 2001.51
  4797.0 2001.77  4817.1 2001.46  4840.0 2001.46  4847.3 2001.70  4922.9 2000.62
  4927.9 2000.96  4958.1 2001.14  4985.8 1999.94  4986.2 1999.44  4990.4 1999.44
  4990.8 1999.94  5017.4 1999.96  5062.6 2002.64  5071.9 2003.83  5086.1 2004.50
  5109.6 2006.53  5115.5 2007.60  5126.4 2008.71  5136.5 2010.26  5156.6 2013.30
  5162.0 2012.82  5180.1 2013.66  5191.7 2013.21  5202.6 2013.76  5209.0 2013.72
#Mann=4,-1,0
  4686.5   0.033       0  4985.8   0.033       0  4990.8   0.033       0
  5136.5   0.035       0
Bank Sta=4985.8,4990.8
Exp/Cntr=0.3,0.1

Chan Stop Cuts=-1