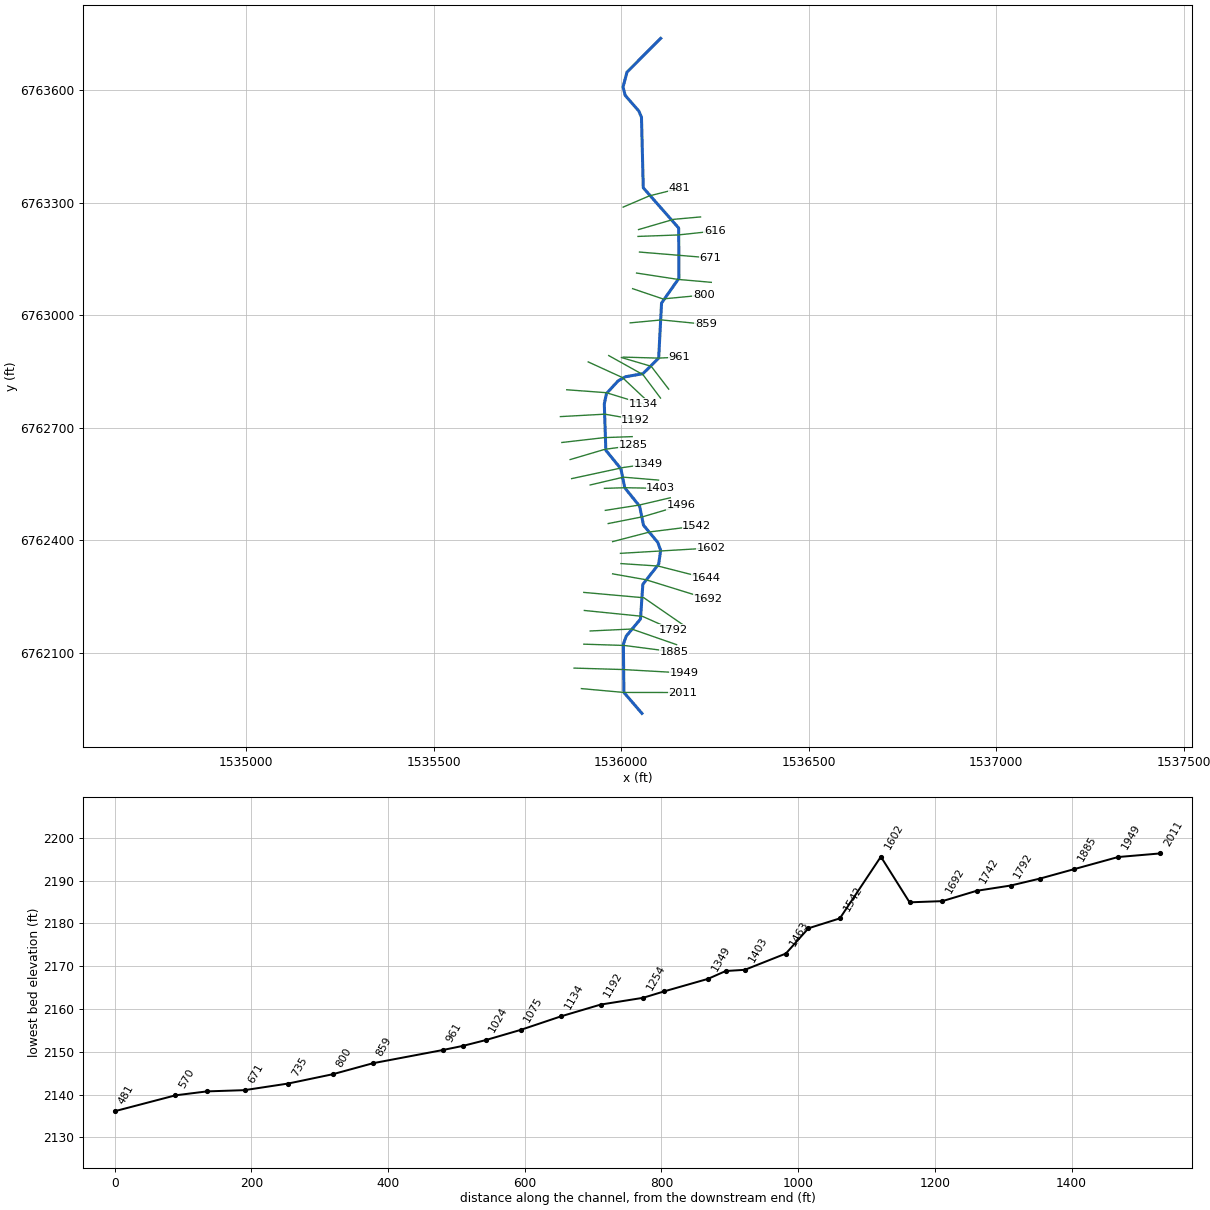
--- Elm 80.prj (project) ---

Proj Title=Elm 80 Base Level Engineering
Current Plan=p01
Default Exp/Contr=0.3,0.1
English Units
Geom File=g01
Flow File=f01
Plan File=p01
BEGIN DESCRIPTION:
Elm 80
END DESCRIPTION:

--- Elm 80.p01 (plan) ---

Plan Title=Multiple Run
Short Identifier=Multiple
Geom File=g01
Flow File=f01
Subcritical Flow
K Sum by GR= 0
Std Step Tol= 0.01
Critical Tol= 0.01
Num of Std Step Trials= 20
Max Error Tol= 0.3
Flow Tol Ratio= 0.001
Split Flow NTrial= 30
Split Flow Tol= 0.02
Split Flow Ratio= 0.02
Log Output Level= 0
Friction Slope Method= 1
Unsteady Friction Slope Method= 2
Unsteady Bridges Friction Slope Method= 1
Parabolic Critical Depth
Global Vel Dist=  1 , 1 , 1
Global Log Level= 0
CheckData=True
Encroach Param= -1, 0, 0, 0
BEGIN DESCRIPTION:
Multiple Run
END DESCRIPTION:

--- Elm 80.f01 (steady flow) ---

Flow Title=Multiple
Number of Profiles=7
Profile Names=10-year,25-year,50-year,1pct_min,100-year,1pct_plu,500-year
River Rch & RM= Elm 80,Reach-1,2011
     147     202     248     190     304     418     462
River Rch & RM= Elm 80,Reach-1,35
     264     374     468     365     584     804     921
Boundary for River Rch & Prof#=Elm 80,Reach-1,1
Up Type=0
Dn Type=3
Dn Slope=0.005
Boundary for River Rch & Prof#=Elm 80,Reach-1,2
Up Type=0
Dn Type=3
Dn Slope=0.005
Boundary for River Rch & Prof#=Elm 80,Reach-1,3
Up Type=0
Dn Type=3
Dn Slope=0.005
Boundary for River Rch & Prof#=Elm 80,Reach-1,4
Up Type=0
Dn Type=3
Dn Slope=0.005
Boundary for River Rch & Prof#=Elm 80,Reach-1,5
Up Type=0
Dn Type=3
Dn Slope=0.005
Boundary for River Rch & Prof#=Elm 80,Reach-1,6
Up Type=0
Dn Type=3
Dn Slope=0.005
Boundary for River Rch & Prof#=Elm 80,Reach-1,7
Up Type=0
Dn Type=3
Dn Slope=0.005

--- Elm 80.g01 (geometry) ---

Geom Title=Existing Conditions

River Reach=Elm 80,Reach-1
Reach XY= 30
      1536055.00      6761938.00      1536006.88      6761993.79
      1536005.50      6762122.78      1536013.13      6762144.06
      1536051.14      6762189.60      1536057.38      6762282.03
      1536099.63      6762335.82      1536104.92      6762372.61
      1536097.23      6762393.94      1536059.22      6762439.72
      1536048.92      6762490.20      1536009.16      6762539.72
      1535998.88      6762590.18      1535958.74      6762639.56
      1535954.64      6762763.20      1535960.35      6762790.70
      1535991.38      6762824.54      1536010.88      6762835.53
      1536057.55      6762843.75      1536099.64      6762885.30
      1536107.27      6763032.06      1536153.79      6763098.51
      1536152.94      6763232.14      1536058.55      6763339.47
      1536053.76      6763527.50      1536046.81      6763544.08
      1536010.35      6763585.83      1536004.62      6763608.20
      1536015.08      6763647.71      1536105.00      6763738.00

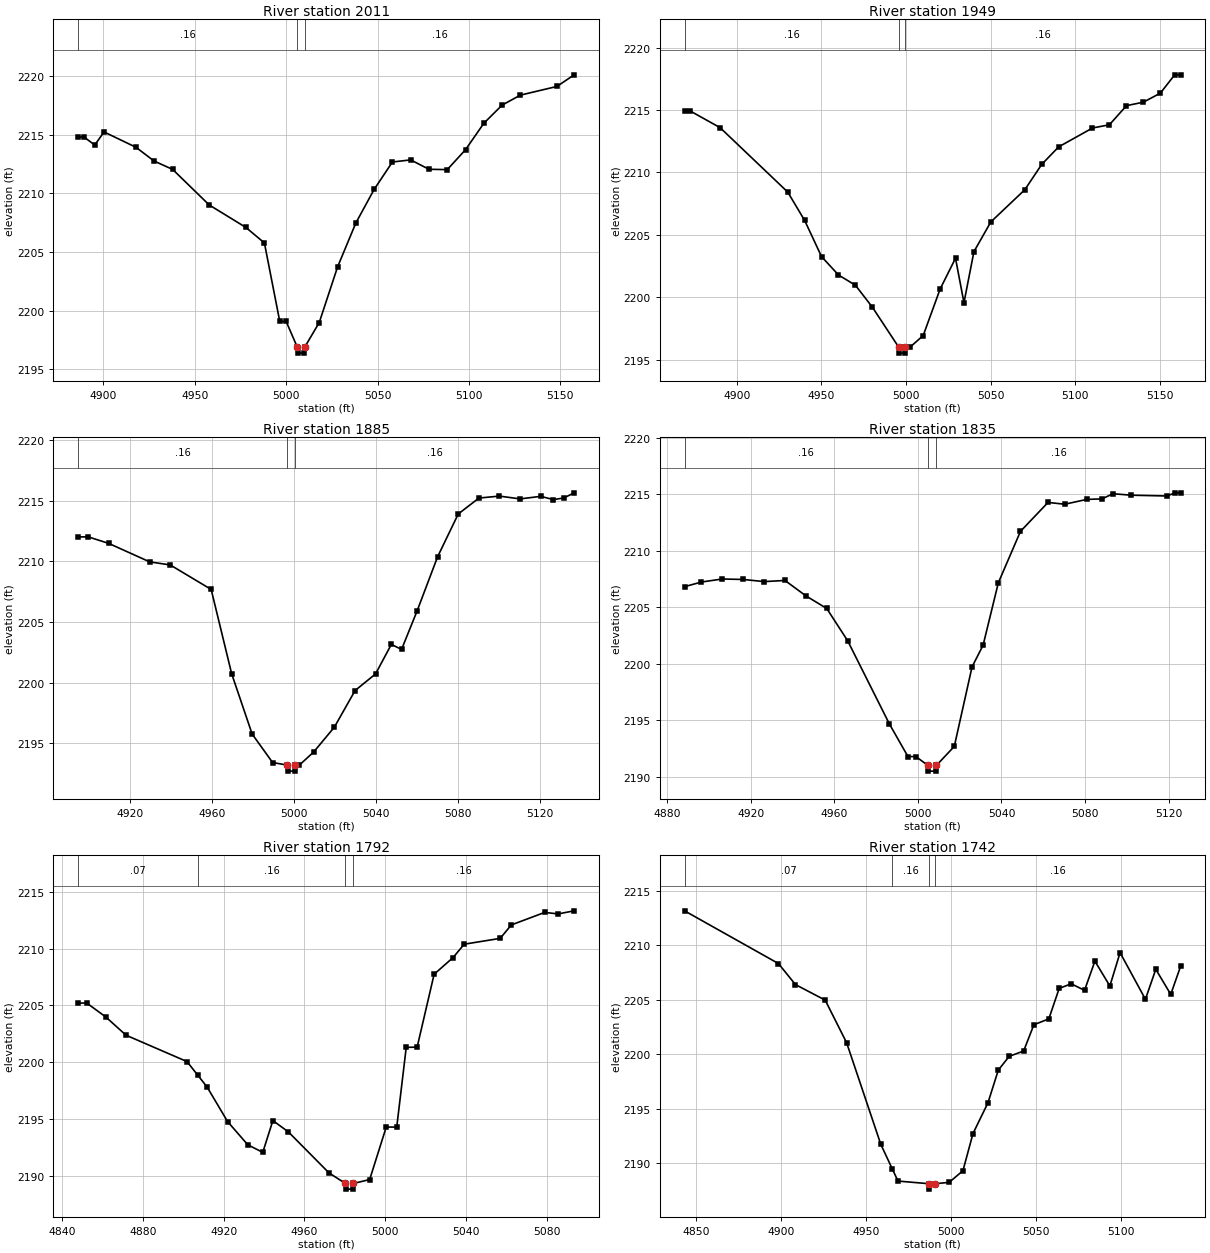
Type RM Length L Ch R = 1,2011,62,62,62
BEGIN DESCRIPTION:
Elm 80 4087
END DESCRIPTION:
XS GIS Cut Line= 3
      1535893.54      6762004.06      1536006.88      6761993.79
      1536164.38      6761993.65
#Sta/Elev= 30
  4886.2 2214.80  4889.4 2214.80  4895.3 2214.12  4900.4 2215.23  4917.8 2213.93
  4927.8 2212.75  4937.9 2212.04  4957.9 2209.01  4978.0 2207.09  4988.1 2205.77
  4996.5 2199.08  5000.0 2199.08  5006.1 2196.88  5006.4 2196.38  5009.9 2196.38
  5010.1 2196.88  5018.1 2198.99  5028.1 2203.72  5038.1 2207.47  5048.1 2210.33
  5058.1 2212.67  5068.1 2212.85  5078.1 2212.05  5088.1 2212.02  5098.1 2213.72
  5108.1 2215.97  5118.1 2217.52  5128.1 2218.37  5148.1 2219.11  5157.5 2220.10
#Mann=3,-1,0
  4886.2    0.16       0  5006.1    0.07       0  5010.1    0.16       0
Bank Sta=5006.1,5010.1
Exp/Cntr=0.3,0.1

Type RM Length L Ch R = 1,1949,64,64,64
BEGIN DESCRIPTION:
Elm 80 4086
END DESCRIPTION:
XS GIS Cut Line= 3
      1535874.01      6762058.75      1536004.85      6762054.88
      1536166.99      6762045.73
#Sta/Elev= 30
  4869.1 2214.95  4872.1 2214.95  4890.1 2213.59  4930.1 2208.43  4940.1 2206.16
  4950.1 2203.26  4960.1 2201.79  4970.1 2200.97  4980.1 2199.22  4995.6 2196.03
  4995.8 2195.53  4999.3 2195.53  4999.6 2196.03  5002.6 2196.03  5010.2 2196.94
  5020.2 2200.66  5029.3 2203.13  5034.3 2199.57  5040.2 2203.66  5050.2 2206.04
  5070.3 2208.62  5080.3 2210.65  5090.3 2212.05  5110.3 2213.56  5120.3 2213.82
  5130.4 2215.35  5140.4 2215.63  5150.4 2216.35  5158.9 2217.82  5162.4 2217.82
#Mann=3,-1,0
  4869.1    0.16       0  4995.6    0.07       0  4999.6    0.16       0
Bank Sta=4995.6,4999.6
Exp/Cntr=0.3,0.1

Type RM Length L Ch R = 1,1885,50,50,50
BEGIN DESCRIPTION:
Elm 80 1881.481
END DESCRIPTION:
XS GIS Cut Line= 3
      1535900.02      6762122.56      1536008.08      6762119.10
      1536141.15      6762101.86
#Sta/Elev= 30
  4894.5 2212.01  4899.5 2212.01  4909.5 2211.47  4929.5 2209.95  4939.5 2209.70
  4959.5 2207.68  4969.5 2200.74  4979.5 2195.77  4989.5 2193.42  4996.6 2193.21
  4996.8 2192.71  5000.3 2192.71  5000.6 2193.21  5002.6 2193.21  5009.6 2194.29
  5019.7 2196.34  5029.8 2199.35  5039.8 2200.72  5047.5 2203.15  5052.5 2202.74
  5060.0 2205.87  5070.1 2210.37  5080.2 2213.90  5090.3 2215.21  5100.3 2215.37
  5110.4 2215.14  5120.5 2215.35  5126.7 2215.08  5131.8 2215.22  5136.8 2215.64
#Mann=3,-1,0
  4894.5    0.16       0  4996.6    0.07       0  5000.6    0.16       0
Bank Sta=4996.6,5000.6
Exp/Cntr=0.3,0.1

Type RM Length L Ch R = 1,1835,43,43,43
BEGIN DESCRIPTION:
Elm 80 1834.74
END DESCRIPTION:
XS GIS Cut Line= 3
      1535916.98      6762157.71      1536027.66      6762162.92
      1536147.42      6762121.26
#Sta/Elev= 30
  4888.2 2206.83  4896.2 2207.24  4906.2 2207.51  4916.3 2207.47  4926.3 2207.28
  4936.3 2207.38  4946.3 2206.02  4956.3 2204.90  4966.3 2202.05  4986.3 2194.68
  4995.2 2191.79  4999.0 2191.79  5004.8 2191.00  5005.0 2190.50  5008.5 2190.50
  5008.8 2191.00  5017.4 2192.69  5025.9 2199.73  5031.2 2201.65  5038.5 2207.18
  5049.1 2211.73  5062.3 2214.29  5070.3 2214.13  5080.9 2214.56  5088.1 2214.60
  5093.4 2215.06  5102.1 2214.93  5119.2 2214.86  5123.2 2215.14  5125.8 2215.14
#Mann=3,-1,0
  4888.2    0.16       0  5004.8    0.07       0  5008.8    0.16       0
Bank Sta=5004.8,5008.8
Exp/Cntr=0.3,0.1

Type RM Length L Ch R = 1,1792,50,50,50
BEGIN DESCRIPTION:
Elm 80 1791.87
END DESCRIPTION:
XS GIS Cut Line= 3
      1535901.39      6762212.40      1536056.31      6762196.77
      1536138.36      6762160.31
#Sta/Elev= 30
  4848.0 2205.21  4852.3 2205.21  4861.7 2203.99  4871.7 2202.39  4901.9 2200.07
  4907.3 2198.86  4911.9 2197.82  4922.0 2194.80  4932.0 2192.76  4939.4 2192.10
  4944.4 2194.89  4952.1 2193.89  4972.2 2190.29  4980.3 2189.37  4980.5 2188.87
  4984.0 2188.87  4984.3 2189.37  4992.3 2189.71  5000.5 2194.32  5005.7 2194.32
  5010.4 2201.32  5015.8 2201.34  5024.2 2207.74  5033.6 2209.21  5039.1 2210.38
  5056.9 2210.89  5062.4 2212.07  5078.9 2213.17  5085.6 2213.04  5093.5 2213.31
#Mann=4,-1,0
  4848.0    0.07       0  4907.3    0.16       0  4980.3    0.07       0
  4984.3    0.16       0
Bank Sta=4980.3,4984.3
Exp/Cntr=0.3,0.1

Type RM Length L Ch R = 1,1742,50,50,50
BEGIN DESCRIPTION:
Elm 80 1742.17
END DESCRIPTION:
XS GIS Cut Line= 3
      1535900.05      6762260.58      1536060.21      6762246.25
      1536167.93      6762171.88
#Sta/Elev= 30
  4843.3 2213.18  4898.5 2208.34  4908.5 2206.41  4926.0 2204.98  4938.6 2201.07
  4958.7 2191.74  4965.5 2189.47  4968.8 2188.37  4986.8 2188.13  4987.1 2187.63
  4990.8 2188.13  4998.9 2188.25  5007.0 2189.32  5012.9 2192.73  5021.7 2195.55
  5027.8 2198.56  5034.2 2199.82  5042.7 2200.31  5048.7 2202.72  5057.5 2203.26
  5063.6 2206.06  5070.7 2206.48  5078.5 2205.88  5084.6 2208.56  5093.4 2206.28
  5099.4 2209.34  5114.3 2205.06  5120.4 2207.81  5129.2 2205.51  5135.0 2208.09
#Mann=4,-1,0
  4843.3    0.07       0  4965.5    0.16       0  4986.8    0.07       0
  4990.8    0.16       0
Bank Sta=4986.8,4990.8
Exp/Cntr=0.3,0.1

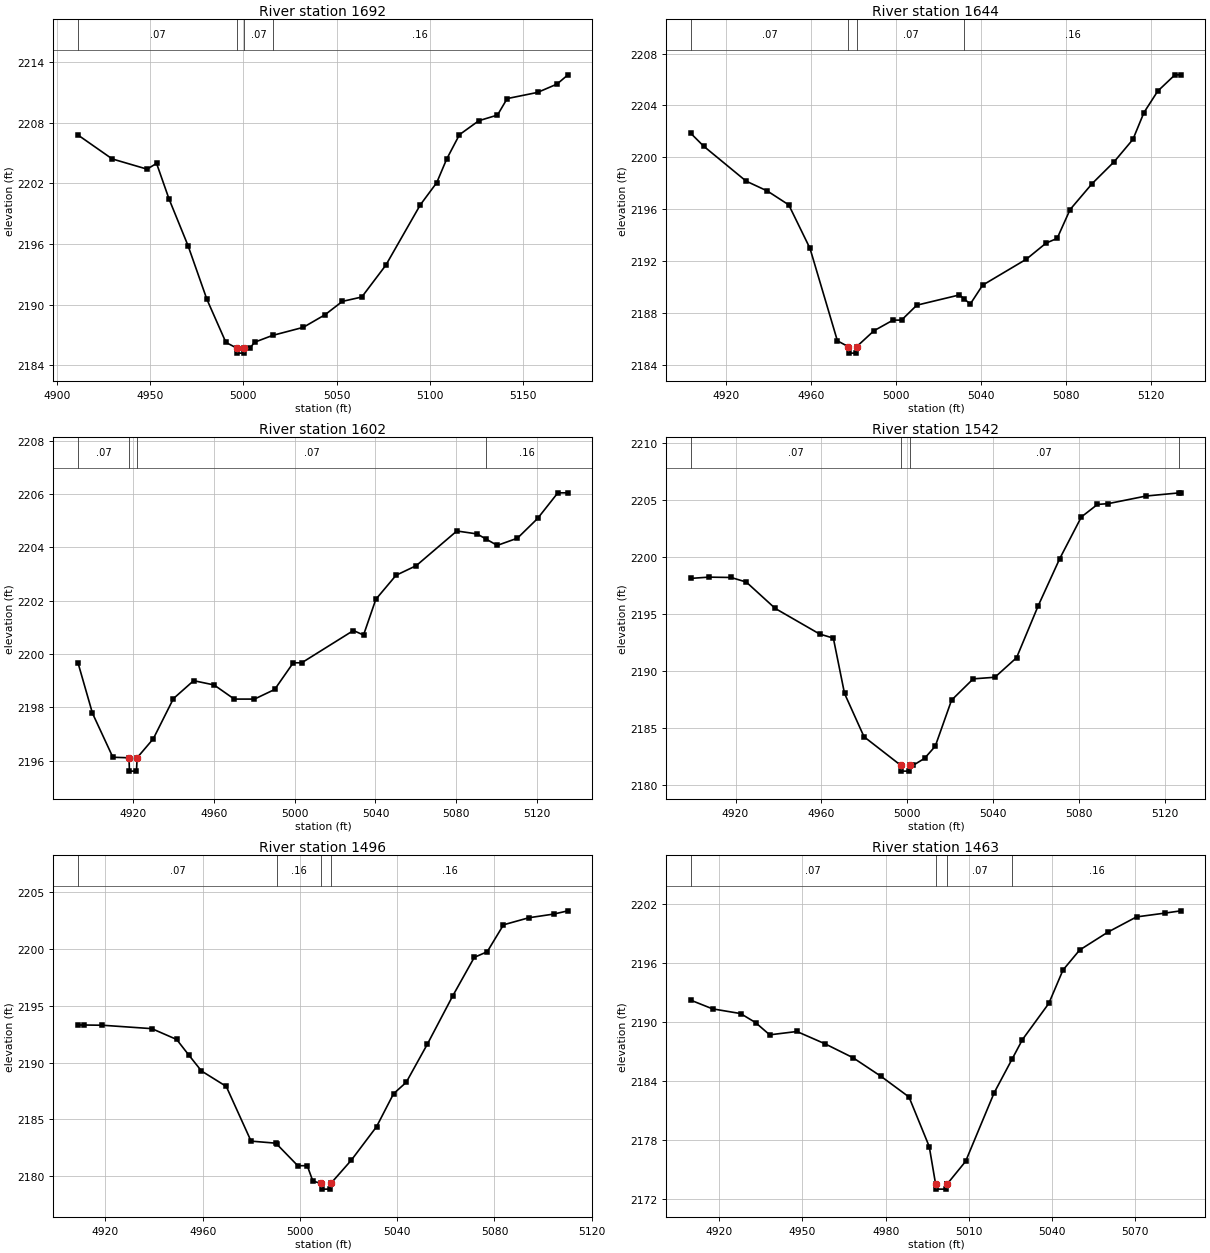
Type RM Length L Ch R = 1,1692,48,48,48
BEGIN DESCRIPTION:
Elm 80 1692.36
END DESCRIPTION:
XS GIS Cut Line= 3
      1535976.84      6762310.06      1536065.42      6762294.43
      1536230.62      6762243.21
#Sta/Elev= 30
  4911.2 2206.80  4929.6 2204.43  4948.3 2203.42  4953.4 2203.99  4960.1 2200.46
  4970.3 2195.84  4980.4 2190.54  4990.6 2186.28  4996.4 2185.72  4996.6 2185.22
  5000.1 2185.22  5000.4 2185.72  5003.5 2185.72  5006.0 2186.30  5015.6 2186.97
  5032.1 2187.77  5043.8 2189.02  5053.1 2190.34  5063.5 2190.77  5076.4 2193.92
  5094.9 2199.89  5103.7 2202.08  5109.0 2204.40  5115.9 2206.83  5126.3 2208.21
  5136.3 2208.77  5141.5 2210.40  5157.8 2211.01  5168.2 2211.83  5174.1 2212.75
#Mann=4,-1,0
  4911.2    0.07       0  4996.4    0.07       0  5000.4    0.07       0
  5015.6    0.16       0
Bank Sta=4996.4,5000.4
Exp/Cntr=0.3,0.1

Type RM Length L Ch R = 1,1644,42,42,42
BEGIN DESCRIPTION:
Elm 80 1644.36
END DESCRIPTION:
XS GIS Cut Line= 3
      1535999.03      6762337.40      1536097.98      6762330.89
      1536225.54      6762298.35
#Sta/Elev= 30
  4903.4 2201.85  4909.4 2200.87  4929.4 2198.18  4939.4 2197.42  4949.5 2196.35
  4959.5 2193.00  4972.4 2185.89  4977.5 2185.44  4977.8 2184.94  4981.3 2184.94
  4981.5 2185.44  4989.6 2186.66  4998.6 2187.48  5002.6 2187.48  5009.8 2188.63
  5029.9 2189.42  5032.2 2189.10  5035.0 2188.72  5040.8 2190.17  5061.4 2192.17
  5070.7 2193.41  5075.9 2193.77  5082.0 2195.99  5092.4 2197.99  5102.7 2199.66
  5111.6 2201.39  5116.8 2203.46  5123.3 2205.11  5131.4 2206.36  5134.2 2206.36
#Mann=4,-1,0
  4903.4    0.07       0  4977.5    0.07       0  4981.5    0.07       0
  5032.2    0.16       0
Bank Sta=4977.5,4981.5
Exp/Cntr=0.3,0.1

Type RM Length L Ch R = 1,1602,60,60,60
BEGIN DESCRIPTION:
Elm 80 1601.97
END DESCRIPTION:
XS GIS Cut Line= 3
      1535997.76      6762364.74      1536108.39      6762371.25
      1536239.94      6762379.07
#Sta/Elev= 29
  4892.7 2199.68  4899.9 2197.78  4910.0 2196.13  4918.0 2196.11  4918.2 2195.61
  4921.7 2195.61  4922.0 2196.11  4930.0 2196.82  4940.0 2198.33  4950.0 2199.00
  4960.1 2198.84  4970.1 2198.31  4980.1 2198.31  4990.1 2198.67  4999.3 2199.67
  5003.5 2199.67  5029.1 2200.88  5034.1 2200.71  5040.2 2202.05  5050.2 2202.95
  5060.2 2203.31  5080.3 2204.61  5090.3 2204.50  5094.7 2204.31  5100.3 2204.07
  5110.3 2204.34  5120.3 2205.08  5130.3 2206.04  5135.3 2206.04
#Mann=4,-1,0
  4892.7    0.07       0  4918.0    0.07       0  4922.0    0.07       0
  5094.7    0.16       0
Bank Sta=4918,4922
Exp/Cntr=0.3,0.1

Type RM Length L Ch R = 1,1542,46,46,46
BEGIN DESCRIPTION:
Elm 80 1542.12
END DESCRIPTION:
XS GIS Cut Line= 3
      1535976.92      6762396.00      1536077.14      6762422.03
      1536201.03      6762437.52
#Sta/Elev= 28
  4899.2 2198.13  4907.5 2198.24  4917.9 2198.21  4925.0 2197.81  4938.5 2195.49
  4959.2 2193.24  4965.6 2192.88  4970.8 2188.02  4979.9 2184.21  4997.1 2181.69
  4997.3 2181.19  5000.8 2181.19  5001.1 2181.69  5002.7 2181.69  5008.1 2182.31
  5013.1 2183.38  5020.7 2187.43  5030.8 2189.30  5040.9 2189.44  5051.0 2191.16
  5061.1 2195.73  5071.1 2199.86  5081.2 2203.53  5088.7 2204.63  5093.7 2204.70
  5111.4 2205.37  5126.5 2205.64  5127.6 2205.65
#Mann=4,-1,0
  4899.2    0.07       0  4997.1    0.07       0  5001.1    0.07       0
  5126.5    0.16       0
Bank Sta=4997.1,5001.1
Exp/Cntr=0.3,0.1

Type RM Length L Ch R = 1,1496,33,33,33
BEGIN DESCRIPTION:
Elm 80 1495.67
END DESCRIPTION:
XS GIS Cut Line= 3
      1535965.14      6762444.16      1536057.61      6762462.40
      1536160.44      6762492.87
#Sta/Elev= 30
  4908.7 2193.30  4911.2 2193.30  4918.8 2193.28  4939.1 2192.98  4949.3 2192.03
  4954.4 2190.63  4959.5 2189.26  4969.7 2187.90  4979.9 2183.09  4990.1 2182.91
  4990.6 2182.80  4999.1 2180.93  5003.0 2180.93  5005.3 2179.58  5008.7 2179.37
  5008.9 2178.87  5012.4 2178.87  5012.7 2179.37  5021.1 2181.41  5031.5 2184.36
  5038.5 2187.26  5043.7 2188.26  5052.4 2191.62  5062.8 2195.85  5071.7 2199.25
  5077.0 2199.74  5083.7 2202.11  5094.1 2202.73  5104.5 2203.06  5110.2 2203.34
#Mann=4,-1,0
  4908.7    0.07       0  4990.6    0.16       0  5008.7    0.07       0
  5012.7    0.16       0
Bank Sta=5008.7,5012.7
Exp/Cntr=0.3,0.1

Type RM Length L Ch R = 1,1463,60,60,60
BEGIN DESCRIPTION:
Elm 80 1462.71
END DESCRIPTION:
XS GIS Cut Line= 3
      1535957.31      6762479.32      1536048.50      6762493.65
      1536130.56      6762512.88
#Sta/Elev= 27
  4909.8 2192.23  4917.6 2191.35  4927.7 2190.87  4933.1 2189.95  4938.2 2188.70
  4948.0 2189.04  4958.1 2187.79  4968.2 2186.37  4978.3 2184.47  4988.4 2182.36
  4995.7 2177.30  4998.0 2173.46  4998.3 2172.96  5001.8 2172.96  5002.0 2173.46
  5002.1 2173.46  5008.8 2175.79  5019.1 2182.79  5025.6 2186.25  5029.3 2188.22
  5038.8 2191.91  5043.9 2195.31  5049.9 2197.35  5060.1 2199.18  5070.4 2200.73
  5080.7 2201.12  5086.4 2201.35
#Mann=4,-1,0
  4909.8    0.07       0  4998.0    0.07       0  5002.0    0.07       0
  5025.6    0.16       0
Bank Sta=4998,5002
Exp/Cntr=0.3,0.1

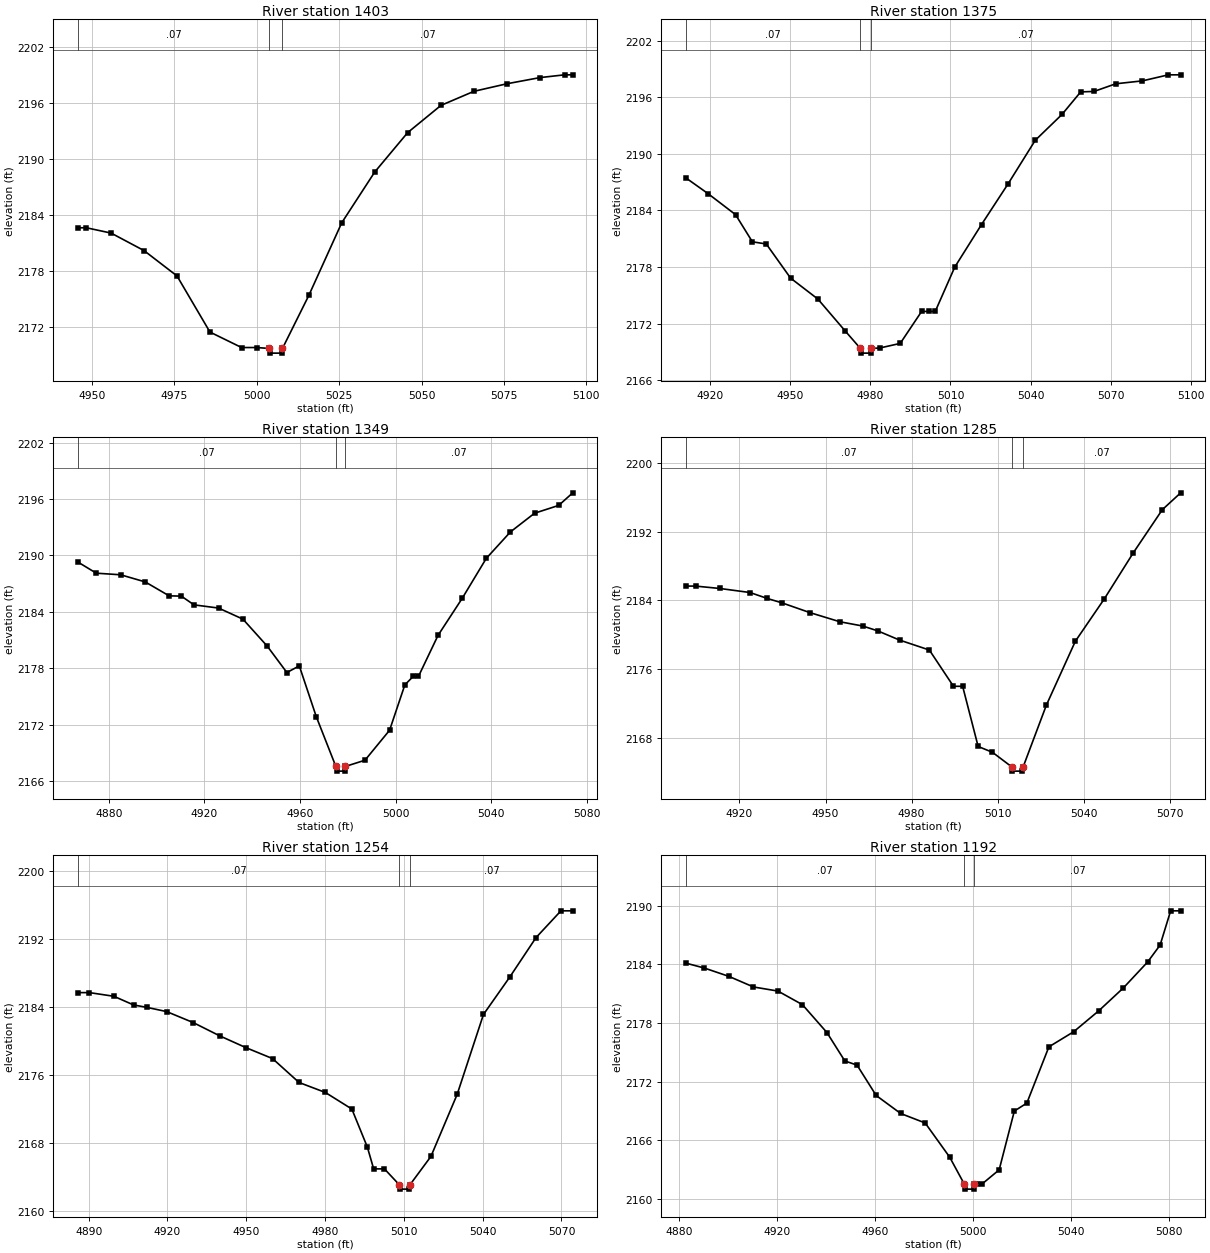
Type RM Length L Ch R = 1,1403,28,28,28
BEGIN DESCRIPTION:
Elm 80 1403.2
END DESCRIPTION:
XS GIS Cut Line= 3
      1535954.99      6762538.00      1536009.16      6762539.72
      1536105.04      6762538.00
#Sta/Elev= 22
  4945.8 2182.61  4948.3 2182.61  4955.8 2182.04  4965.8 2180.16  4975.8 2177.44
  4985.8 2171.42  4995.4 2169.76  5000.0 2169.76  5003.8 2169.66  5004.1 2169.16
  5007.6 2169.16  5007.8 2169.66  5015.8 2175.35  5025.8 2183.15  5035.8 2188.59
  5045.8 2192.82  5055.9 2195.74  5065.9 2197.25  5075.9 2198.06  5085.9 2198.72
  5093.4 2199.02  5095.9 2199.02
#Mann=3,-1,0
  4945.8    0.07       0  5003.8    0.07       0  5007.8    0.07       0
Bank Sta=5003.8,5007.8
Exp/Cntr=0.3,0.1

Type RM Length L Ch R = 1,1375,26,26,26
BEGIN DESCRIPTION:
Elm 80 1374.96
END DESCRIPTION:
XS GIS Cut Line= 3
      1535916.98      6762547.03      1536005.53      6762567.87
      1536099.24      6762560.06
#Sta/Elev= 28
  4911.1 2187.44  4919.3 2185.79  4929.6 2183.56  4935.9 2180.68  4941.1 2180.45
  4950.2 2176.83  4960.4 2174.61  4970.7 2171.20  4976.3 2169.38  4976.6 2168.88
  4980.1 2168.88  4980.3 2169.38  4983.5 2169.42  4991.2 2169.91  4999.2 2173.30
  5002.1 2173.30  5004.3 2173.30  5011.6 2178.00  5021.6 2182.51  5031.6 2186.85
  5041.7 2191.44  5051.7 2194.18  5058.7 2196.57  5063.7 2196.62  5071.8 2197.43
  5081.8 2197.74  5091.5 2198.38  5096.1 2198.38
#Mann=3,-1,0
  4911.1    0.07       0  4976.3    0.07       0  4980.3    0.07       0
Bank Sta=4976.3,4980.3
Exp/Cntr=0.3,0.1

Type RM Length L Ch R = 1,1349,64,64,64
BEGIN DESCRIPTION:
Elm 80 1349.49
END DESCRIPTION:
XS GIS Cut Line= 3
      1535867.55      6762563.97      1536006.83      6762593.91
      1536070.84      6762602.87
#Sta/Elev= 29
  4867.1 2189.27  4874.7 2188.10  4884.9 2187.93  4895.2 2187.17  4905.2 2185.69
  4910.3 2185.66  4915.6 2184.73  4925.9 2184.39  4936.1 2183.21  4946.3 2180.33
  4954.5 2177.53  4959.7 2178.24  4966.8 2172.84  4975.0 2167.54  4975.3 2167.04
  4978.8 2167.04  4979.0 2167.54  4987.2 2168.20  4997.5 2171.39  5003.9 2176.22
  5007.4 2177.12  5009.6 2177.12  5017.8 2181.49  5027.9 2185.42  5038.0 2189.68
  5048.1 2192.49  5058.2 2194.48  5068.3 2195.31  5074.2 2196.65
#Mann=3,-1,0
  4867.1    0.07       0  4975.0    0.07       0  4979.0    0.07       0
Bank Sta=4975,4979
Exp/Cntr=0.3,0.1

Type RM Length L Ch R = 1,1285,31,31,31
BEGIN DESCRIPTION:
Elm 80 1285.21
END DESCRIPTION:
XS GIS Cut Line= 3
      1535863.64      6762614.75      1535956.05      6762642.09
      1536031.39      6762652.30
#Sta/Elev= 26
  4901.4 2185.65  4904.7 2185.65  4913.2 2185.37  4923.7 2184.90  4929.7 2184.21
  4934.9 2183.69  4944.5 2182.57  4955.0 2181.50  4963.0 2181.00  4968.2 2180.44
  4975.8 2179.37  4986.2 2178.21  4994.6 2173.99  4997.8 2173.99  5003.2 2166.99
  5008.2 2166.31  5014.9 2164.62  5015.1 2164.12  5018.6 2164.12  5018.9 2164.62
  5027.0 2171.81  5037.1 2179.24  5047.2 2184.17  5057.3 2189.53  5067.4 2194.54
  5073.8 2196.50
#Mann=3,-1,0
  4901.4    0.07       0  5014.9    0.07       0  5018.9    0.07       0
Bank Sta=5014.9,5018.9
Exp/Cntr=0.3,0.1

Type RM Length L Ch R = 1,1254,62,62,62
BEGIN DESCRIPTION:
Elm 80 1253.96
END DESCRIPTION:
XS GIS Cut Line= 3
      1535841.50      6762660.32      1535954.75      6762673.34
      1536029.00      6762675.94
#Sta/Elev= 27
  4886.0 2185.70  4890.3 2185.70  4899.6 2185.27  4907.1 2184.25  4912.1 2183.97
  4919.7 2183.47  4929.8 2182.18  4939.9 2180.62  4949.9 2179.23  4960.0 2177.95
  4970.1 2175.14  4980.1 2173.97  4990.2 2172.02  4996.1 2167.55  4998.5 2164.99
  5002.6 2164.99  5008.3 2163.11  5008.5 2162.61  5012.0 2162.61  5012.3 2163.11
  5020.3 2166.45  5030.3 2173.75  5040.3 2183.13  5050.3 2187.52  5060.3 2192.16
  5069.8 2195.31  5074.3 2195.31
#Mann=3,-1,0
  4886.0    0.07       0  5008.3    0.07       0  5012.3    0.07       0
Bank Sta=5008.3,5012.3
Exp/Cntr=0.3,0.1

Type RM Length L Ch R = 1,1192,58,58,58
BEGIN DESCRIPTION:
Elm 80 1191.54
END DESCRIPTION:
XS GIS Cut Line= 3
      1535837.55      6762729.32      1535956.05      6762735.84
      1536038.03      6762721.52
#Sta/Elev= 30
  4882.7 2184.12  4890.2 2183.62  4900.2 2182.77  4910.2 2181.69  4920.2 2181.27
  4930.2 2179.88  4940.2 2177.03  4947.5 2174.13  4952.5 2173.70  4960.3 2170.60
  4970.3 2168.76  4980.3 2167.79  4990.3 2164.30  4996.3 2161.53  4996.6 2161.03
  5000.1 2161.03  5000.3 2161.53  5001.4 2161.53  5003.4 2161.53  5010.5 2163.00
  5016.7 2169.01  5021.8 2169.82  5030.8 2175.57  5040.9 2177.11  5051.1 2179.24
  5061.2 2181.59  5071.1 2184.24  5076.2 2185.97  5080.5 2189.47  5084.6 2189.47
#Mann=3,-1,0
  4882.7    0.07       0  4996.3    0.07       0  5000.3    0.07       0
Bank Sta=4996.3,5000.3
Exp/Cntr=0.3,0.1

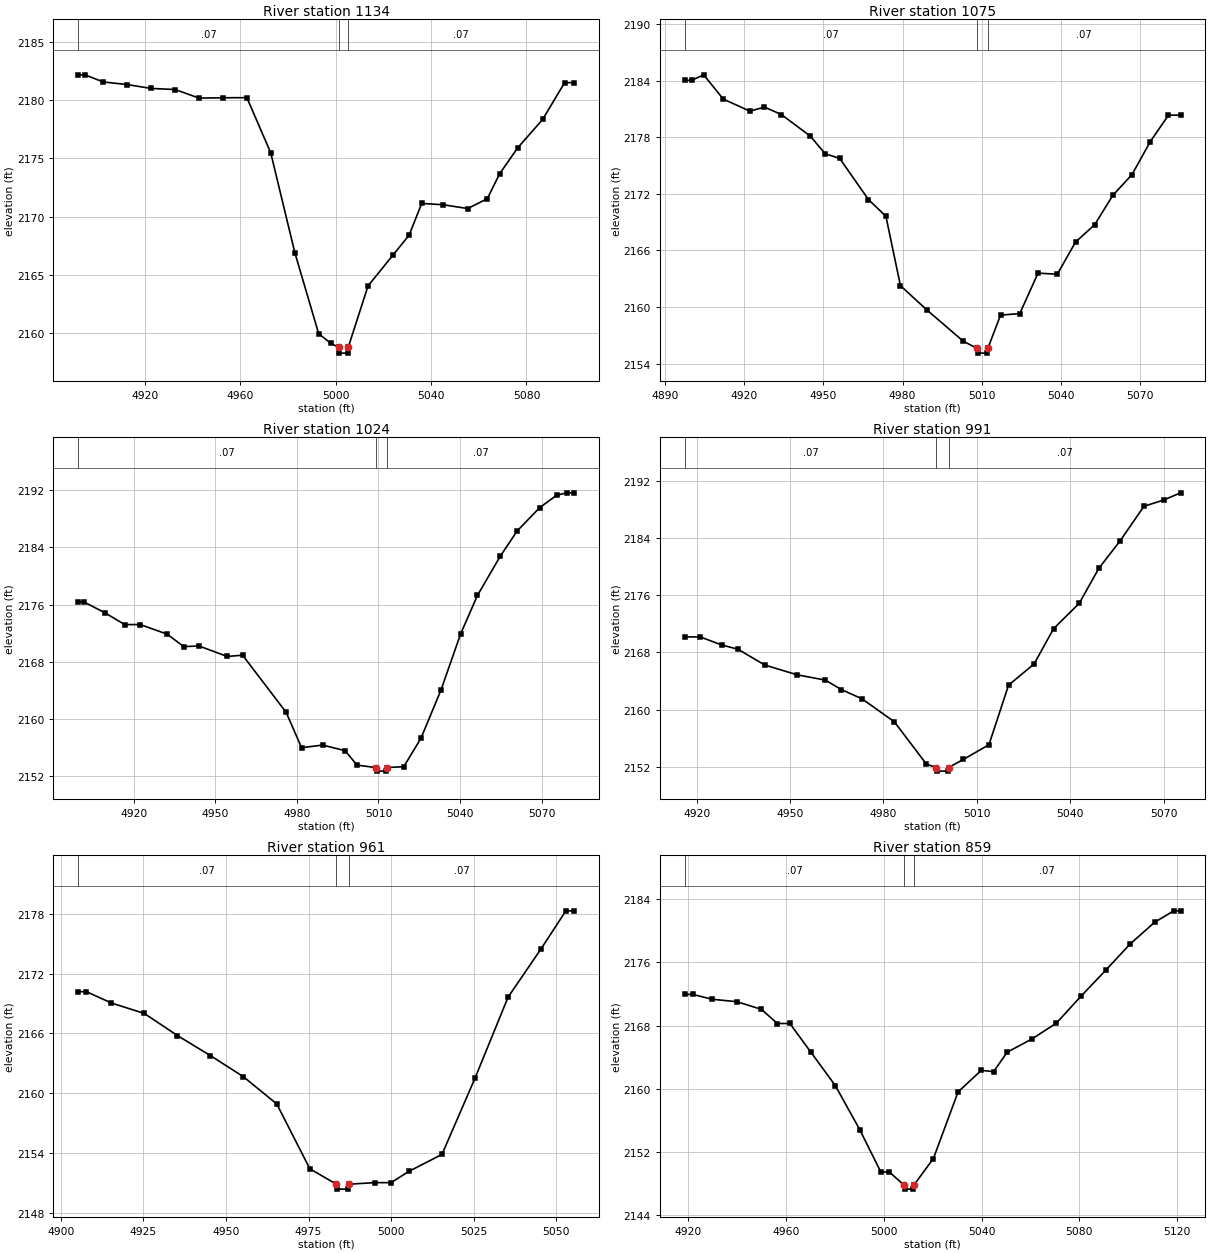
Type RM Length L Ch R = 1,1134,59,59,59
BEGIN DESCRIPTION:
Elm 80 1133.57
END DESCRIPTION:
XS GIS Cut Line= 3
      1535854.49      6762800.94      1535959.95      6762793.13
      1536057.61      6762763.18
#Sta/Elev= 29
  4892.1 2182.17  4894.9 2182.17  4902.6 2181.56  4912.7 2181.33  4922.7 2181.00
  4932.7 2180.91  4942.8 2180.17  4952.8 2180.20  4962.8 2180.21  4972.8 2175.48
  4982.9 2166.91  4992.9 2159.95  4997.9 2159.13  5001.3 2158.78  5001.6 2158.28
  5005.1 2158.28  5005.3 2158.78  5013.6 2164.05  5024.1 2166.71  5030.8 2168.40
  5036.1 2171.13  5045.0 2171.02  5055.4 2170.69  5063.6 2171.54  5068.8 2173.69
  5076.4 2175.92  5086.8 2178.34  5096.0 2181.50  5100.0 2181.50
#Mann=3,-1,0
  4892.1    0.07       0  5001.3    0.07       0  5005.3    0.07       0
Bank Sta=5001.3,5005.3
Exp/Cntr=0.3,0.1

Type RM Length L Ch R = 1,1075,51,51,51
BEGIN DESCRIPTION:
Elm 80 1074.98
END DESCRIPTION:
XS GIS Cut Line= 3
      1535911.73      6762875.18      1536002.92      6762833.49
      1536066.74      6762773.58
#Sta/Elev= 30
  4897.5 2184.05  4900.1 2184.05  4904.7 2184.64  4912.1 2182.07  4922.2 2180.78
  4927.7 2181.22  4934.1 2180.43  4945.1 2178.13  4950.7 2176.27  4956.2 2175.77
  4967.1 2171.40  4973.7 2169.63  4979.2 2162.27  4989.1 2159.72  5003.0 2156.37
  5008.3 2155.61  5008.5 2155.11  5012.0 2155.11  5012.3 2155.61  5017.1 2159.14
  5024.4 2159.31  5031.3 2163.60  5038.6 2163.48  5045.5 2166.89  5052.8 2168.75
  5059.6 2171.84  5066.9 2174.06  5073.8 2177.55  5080.7 2180.36  5085.3 2180.36
#Mann=3,-1,0
  4897.5    0.07       0  5008.3    0.07       0  5012.3    0.07       0
Bank Sta=5008.3,5012.3
Exp/Cntr=0.3,0.1

Type RM Length L Ch R = 1,1024,33,33,33
BEGIN DESCRIPTION:
Elm 80 1023.66
END DESCRIPTION:
XS GIS Cut Line= 3
      1535966.47      6762892.08      1536057.61      6762841.30
      1536104.51      6762778.77
#Sta/Elev= 30
  4899.5 2176.38  4901.5 2176.38  4909.3 2174.85  4916.6 2173.20  4922.3 2173.20
  4932.2 2171.87  4938.3 2170.13  4944.0 2170.20  4954.3 2168.75  4960.0 2168.92
  4976.0 2160.95  4981.7 2156.00  4989.4 2156.37  4997.7 2155.59  5002.1 2153.57
  5009.0 2153.23  5009.3 2152.73  5012.8 2152.73  5013.0 2153.23  5019.3 2153.35
  5025.6 2157.30  5033.0 2164.06  5040.2 2171.87  5046.4 2177.26  5054.8 2182.74
  5061.0 2186.26  5069.3 2189.53  5075.6 2191.27  5079.3 2191.60  5082.0 2191.60
#Mann=3,-1,0
  4899.5    0.07       0  5009.0    0.07       0  5013.0    0.07       0
Bank Sta=5009,5013
Exp/Cntr=0.3,0.1

Type RM Length L Ch R = 1,991,30,30,30
BEGIN DESCRIPTION:
Elm 80 990.67
END DESCRIPTION:
XS GIS Cut Line= 3
      1536000.35      6762886.87      1536079.75      6762863.44
      1536126.34      6762802.61
#Sta/Elev= 26
  4916.1 2170.18  4921.1 2170.18  4928.0 2169.05  4933.2 2168.46  4941.8 2166.25
  4952.2 2164.88  4961.3 2164.13  4966.5 2162.80  4973.1 2161.51  4983.5 2158.29
  4993.8 2152.37  4996.9 2151.89  4997.1 2151.39  5000.6 2151.39  5000.9 2151.89
  5005.7 2153.03  5013.9 2155.09  5020.2 2163.43  5028.4 2166.39  5034.7 2171.35
  5042.9 2174.87  5049.2 2179.77  5056.1 2183.65  5063.7 2188.46  5070.0 2189.34
  5075.5 2190.35
#Mann=3,-1,0
  4916.1    0.07       0  4996.9    0.07       0  5000.9    0.07       0
Bank Sta=4996.9,5000.9
Exp/Cntr=0.3,0.1

Type RM Length L Ch R = 1,961,102,102,102
BEGIN DESCRIPTION:
Elm 80 960.896
END DESCRIPTION:
XS GIS Cut Line= 3
      1536004.97      6762888.00      1536099.64      6762885.30
      1536154.97      6762888.00
#Sta/Elev= 22
  4905.3 2170.18  4907.8 2170.18  4915.3 2169.05  4925.3 2168.00  4935.3 2165.79
  4945.3 2163.78  4955.3 2161.66  4965.4 2158.93  4975.4 2152.44  4983.4 2150.90
  4983.6 2150.40  4987.1 2150.40  4987.4 2150.90  4995.2 2151.05  5000.0 2151.05
  5005.4 2152.18  5015.4 2153.88  5025.4 2161.52  5035.4 2169.63  5045.4 2174.48
  5052.9 2178.28  5055.4 2178.28
#Mann=3,-1,0
  4905.3    0.07       0  4983.4    0.07       0  4987.4    0.07       0
Bank Sta=4983.4,4987.4
Exp/Cntr=0.3,0.1

Type RM Length L Ch R = 1,859,59,59,59
BEGIN DESCRIPTION:
Elm 80 858.64
END DESCRIPTION:
XS GIS Cut Line= 3
      1536023.71      6762979.32      1536107.09      6762987.14
      1536225.57      6762975.42
#Sta/Elev= 29
  4918.6 2171.96  4921.8 2171.96  4929.9 2171.34  4940.0 2171.03  4950.0 2170.06
  4956.5 2168.27  4961.6 2168.28  4970.1 2164.69  4980.2 2160.42  4990.2 2154.84
  4998.8 2149.49  5002.3 2149.49  5008.3 2147.82  5008.5 2147.32  5012.0 2147.32
  5012.3 2147.82  5020.3 2151.19  5030.4 2159.62  5039.9 2162.35  5044.9 2162.18
  5050.5 2164.65  5060.5 2166.30  5070.6 2168.32  5080.6 2171.71  5090.7 2174.99
  5100.7 2178.32  5110.8 2181.09  5118.6 2182.53  5121.4 2182.53
#Mann=3,-1,0
  4918.6    0.07       0  5008.3    0.07       0  5012.3    0.07       0
Bank Sta=5008.3,5012.3
Exp/Cntr=0.3,0.1

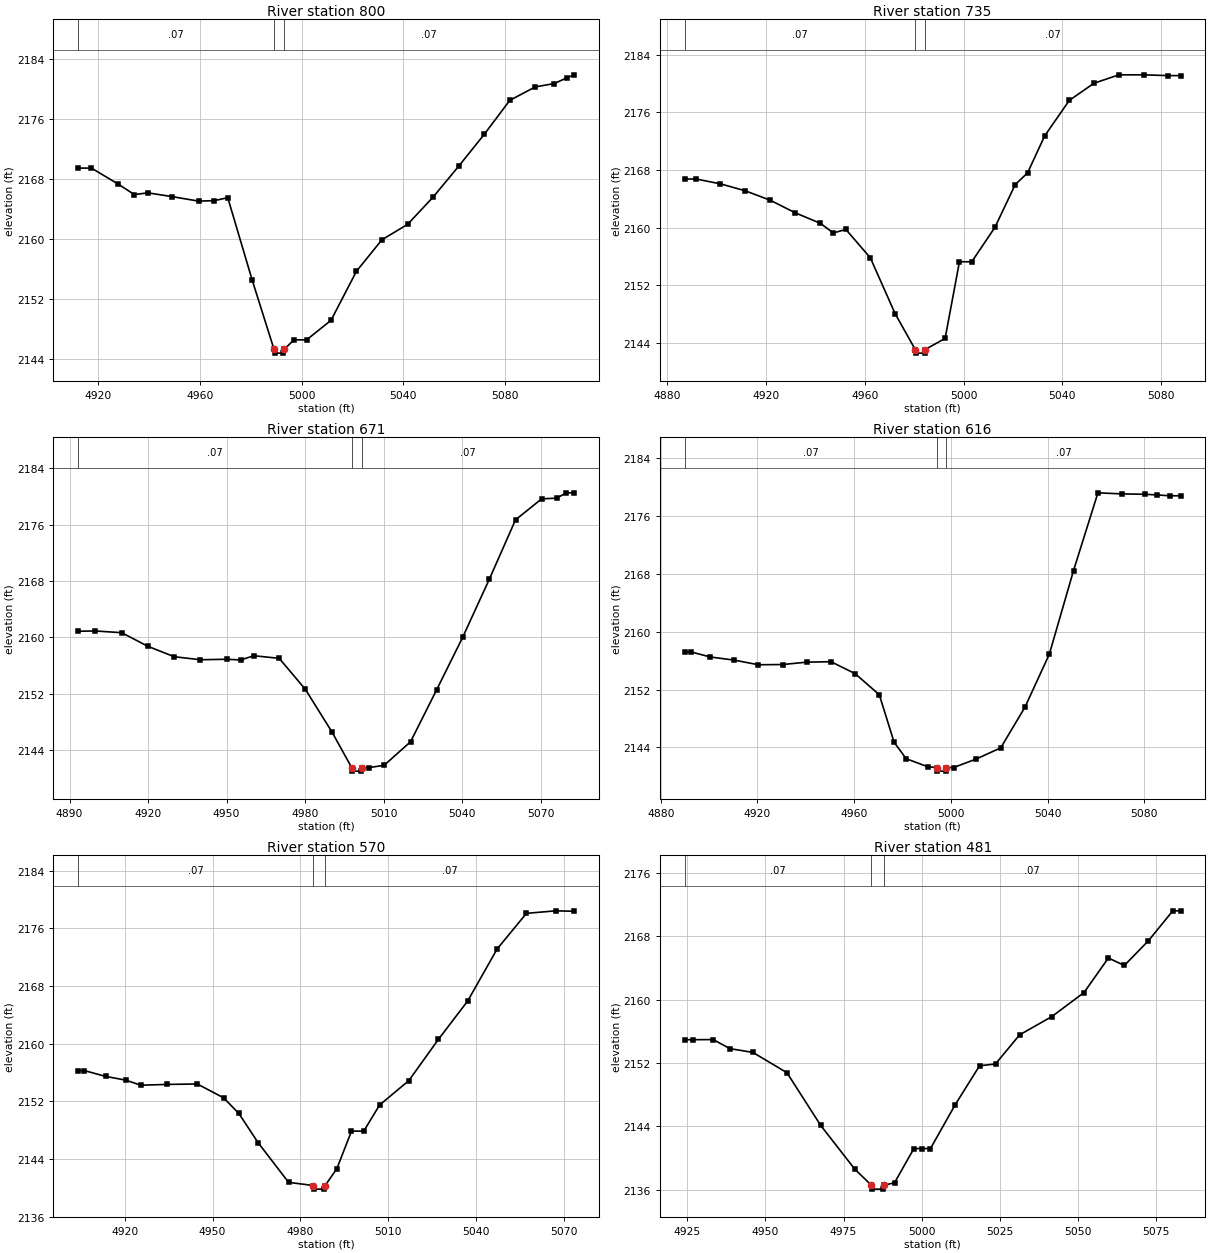
Type RM Length L Ch R = 1,800,65,65,65
BEGIN DESCRIPTION:
Elm 80 800.45
END DESCRIPTION:
XS GIS Cut Line= 3
      1536030.22      6763070.49      1536111.00      6763043.13
      1536220.22      6763053.53
#Sta/Elev= 28
  4912.2 2169.40  4917.4 2169.40  4927.8 2167.29  4934.3 2165.87  4939.6 2166.10
  4948.9 2165.61  4959.5 2165.00  4965.7 2165.06  4971.0 2165.46  4980.6 2154.48
  4989.2 2145.24  4989.4 2144.74  4992.9 2144.74  4993.2 2145.24  4997.0 2146.51
  5002.0 2146.51  5011.6 2149.11  5021.6 2155.65  5031.6 2159.84  5041.7 2161.90
  5051.7 2165.52  5061.8 2169.65  5071.8 2173.88  5081.9 2178.43  5091.9 2180.22
  5099.3 2180.66  5104.3 2181.42  5107.2 2181.83
#Mann=3,-1,0
  4912.2    0.07       0  4989.2    0.07       0  4993.2    0.07       0
Bank Sta=4989.2,4993.2
Exp/Cntr=0.3,0.1

Type RM Length L Ch R = 1,735,64,64,64
BEGIN DESCRIPTION:
Elm 80 735.04
END DESCRIPTION:
XS GIS Cut Line= 3
      1536040.67      6763112.14      1536151.36      6763095.21
      1536239.94      6763087.39
#Sta/Elev= 28
  4887.0 2166.73  4891.7 2166.73  4901.5 2166.06  4911.6 2165.09  4921.7 2163.78
  4931.8 2162.04  4942.0 2160.58  4947.2 2159.25  4952.3 2159.73  4962.2 2155.80
  4972.3 2148.01  4980.4 2143.07  4980.7 2142.57  4984.2 2142.57  4984.4 2143.07
  4992.5 2144.61  4998.3 2155.25  5003.3 2155.25  5012.7 2160.04  5020.9 2165.96
  5025.9 2167.58  5032.8 2172.70  5042.8 2177.64  5052.8 2180.02  5062.9 2181.19
  5072.9 2181.19  5082.9 2181.08  5087.9 2181.08
#Mann=3,-1,0
  4887.0    0.07       0  4980.4    0.07       0  4984.4    0.07       0
Bank Sta=4980.4,4984.4
Exp/Cntr=0.3,0.1

Type RM Length L Ch R = 1,671,55,55,55
BEGIN DESCRIPTION:
Elm 80 670.5
END DESCRIPTION:
XS GIS Cut Line= 3
      1536048.46      6763168.13      1536159.17      6763159.01
      1536237.32      6763152.50
#Sta/Elev= 27
  4893.3 2160.87  4899.9 2160.90  4909.9 2160.66  4919.9 2158.73  4930.0 2157.25
  4940.0 2156.82  4950.0 2156.89  4955.4 2156.79  4960.4 2157.39  4970.1 2157.02
  4980.1 2152.62  4990.2 2146.61  4997.8 2141.52  4998.0 2141.02  5001.5 2141.02
  5001.8 2141.52  5004.4 2141.52  5010.2 2141.85  5020.3 2145.19  5030.3 2152.59
  5040.3 2160.08  5050.4 2168.26  5060.4 2176.67  5070.4 2179.65  5076.1 2179.74
  5079.8 2180.50  5082.8 2180.50
#Mann=3,-1,0
  4893.3    0.07       0  4997.8    0.07       0  5001.8    0.07       0
Bank Sta=4997.8,5001.8
Exp/Cntr=0.3,0.1

Type RM Length L Ch R = 1,616,46,46,46
BEGIN DESCRIPTION:
Elm 80 615.78
END DESCRIPTION:
XS GIS Cut Line= 3
      1536044.55      6763209.79      1536151.36      6763213.70
      1536249.02      6763224.12
#Sta/Elev= 29
  4889.9 2157.22  4892.6 2157.22  4900.4 2156.53  4910.4 2156.09  4920.4 2155.45
  4930.4 2155.48  4940.4 2155.81  4950.4 2155.87  4960.4 2154.22  4970.4 2151.29
  4976.5 2144.73  4981.5 2142.45  4990.4 2141.34  4994.1 2141.23  4994.4 2140.73
  4997.9 2140.73  4998.1 2141.23  5001.1 2141.23  5010.5 2142.41  5020.6 2143.95
  5030.6 2149.56  5040.7 2156.91  5050.7 2168.47  5060.8 2179.24  5070.8 2179.09
  5080.2 2179.04  5085.2 2178.95  5090.5 2178.83  5095.0 2178.83
#Mann=3,-1,0
  4889.9    0.07       0  4994.1    0.07       0  4998.1    0.07       0
Bank Sta=4994.1,4998.1
Exp/Cntr=0.3,0.1

Type RM Length L Ch R = 1,570,89,89,89
BEGIN DESCRIPTION:
Elm 80 570.26
END DESCRIPTION:
XS GIS Cut Line= 3
      1536045.94      6763228.04      1536139.64      6763255.37
      1536211.25      6763261.76
#Sta/Elev= 26
  4904.1 2156.26  4906.2 2156.26  4913.5 2155.45  4920.3 2154.94  4925.5 2154.23
  4934.4 2154.34  4944.8 2154.40  4953.8 2152.48  4959.0 2150.31  4965.6 2146.25
  4976.0 2140.75  4984.5 2140.31  4984.7 2139.81  4988.2 2139.81  4988.5 2140.31
  4992.5 2142.65  4997.5 2147.86  5001.7 2147.86  5007.1 2151.48  5017.1 2154.87
  5027.2 2160.59  5037.2 2165.91  5047.3 2173.15  5057.3 2178.08  5067.3 2178.43
  5073.6 2178.37
#Mann=3,-1,0
  4904.1    0.07       0  4984.5    0.07       0  4988.5    0.07       0
Bank Sta=4984.5,4988.5
Exp/Cntr=0.3,0.1

Type RM Length L Ch R = 1,481,46,46,46
BEGIN DESCRIPTION:
Elm 80 480.937
END DESCRIPTION:
XS GIS Cut Line= 3
      1536004.98      6763287.99      1536074.65      6763317.85
      1536154.96      6763337.99
#Sta/Elev= 27
  4924.2 2154.95  4926.9 2154.95  4933.3 2154.97  4938.7 2153.82  4946.0 2153.35
  4956.9 2150.79  4967.7 2144.13  4978.6 2138.61  4983.9 2136.59  4984.1 2136.09
  4987.6 2136.09  4987.9 2136.59  4991.3 2136.89  4997.5 2141.21  5000.0 2141.21
  5002.8 2141.21  5010.7 2146.74  5018.5 2151.66  5023.6 2151.89  5031.3 2155.56
  5041.6 2157.87  5051.9 2160.90  5059.7 2165.27  5064.8 2164.32  5072.5 2167.44
  5080.3 2171.22  5082.8 2171.22
#Mann=3,-1,0
  4924.2    0.07       0  4983.9    0.07       0  4987.9    0.07       0
Bank Sta=4983.9,4987.9
Exp/Cntr=0.3,0.1