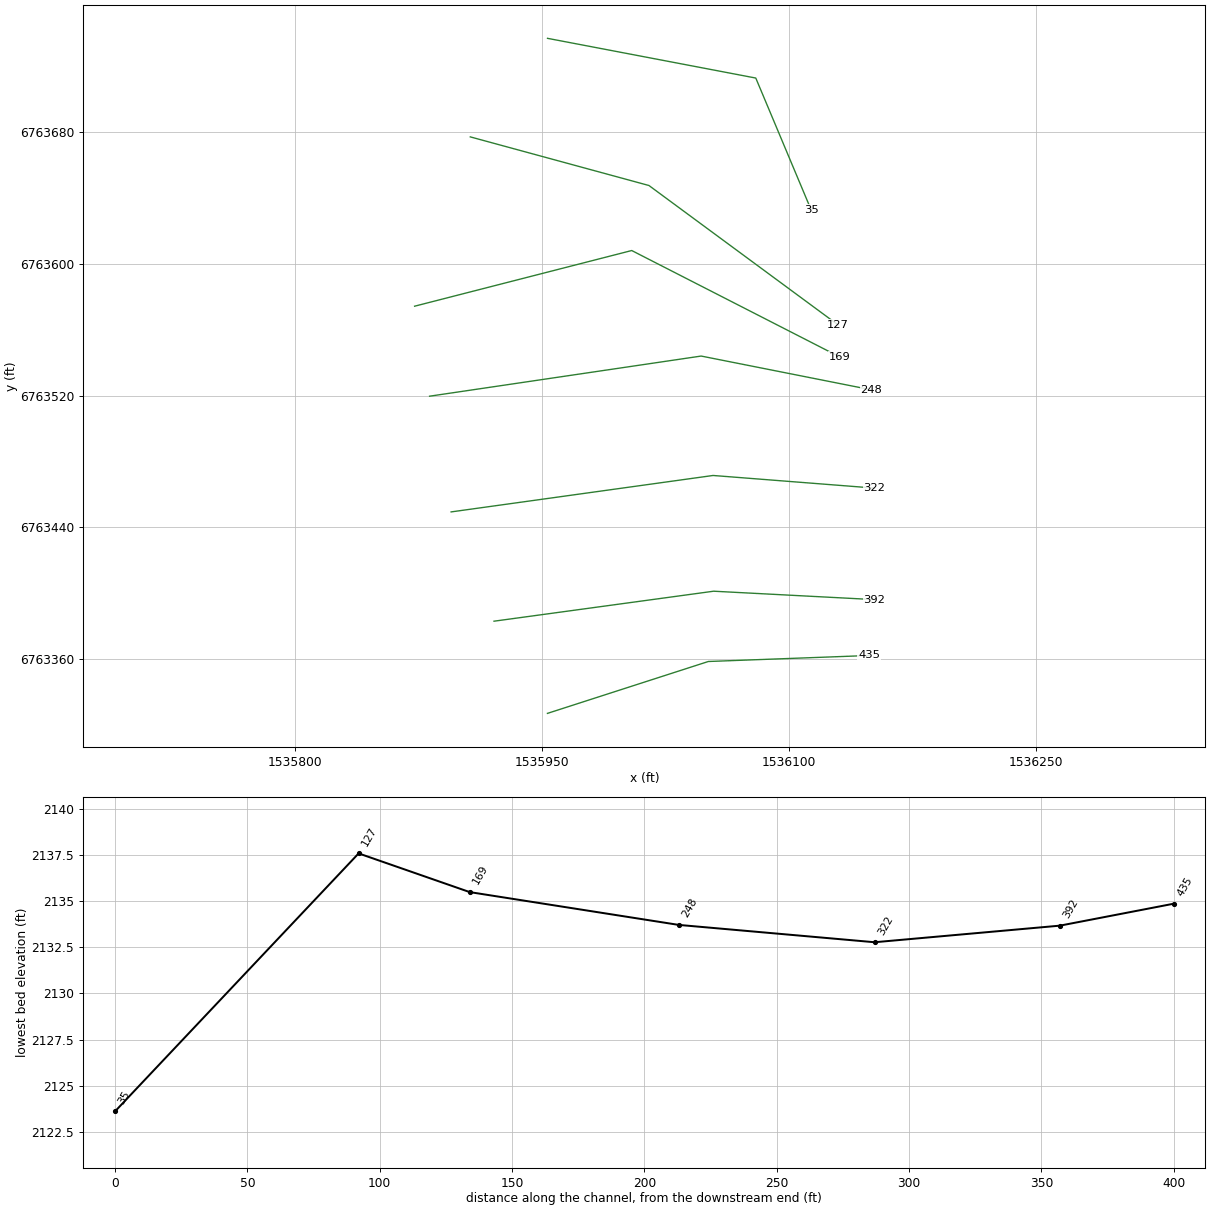
HEC-RAS study Elm 80.prj: Elm 80 Base Level Engineering

--- Elm 80.g01 (geometry) --- (continued)

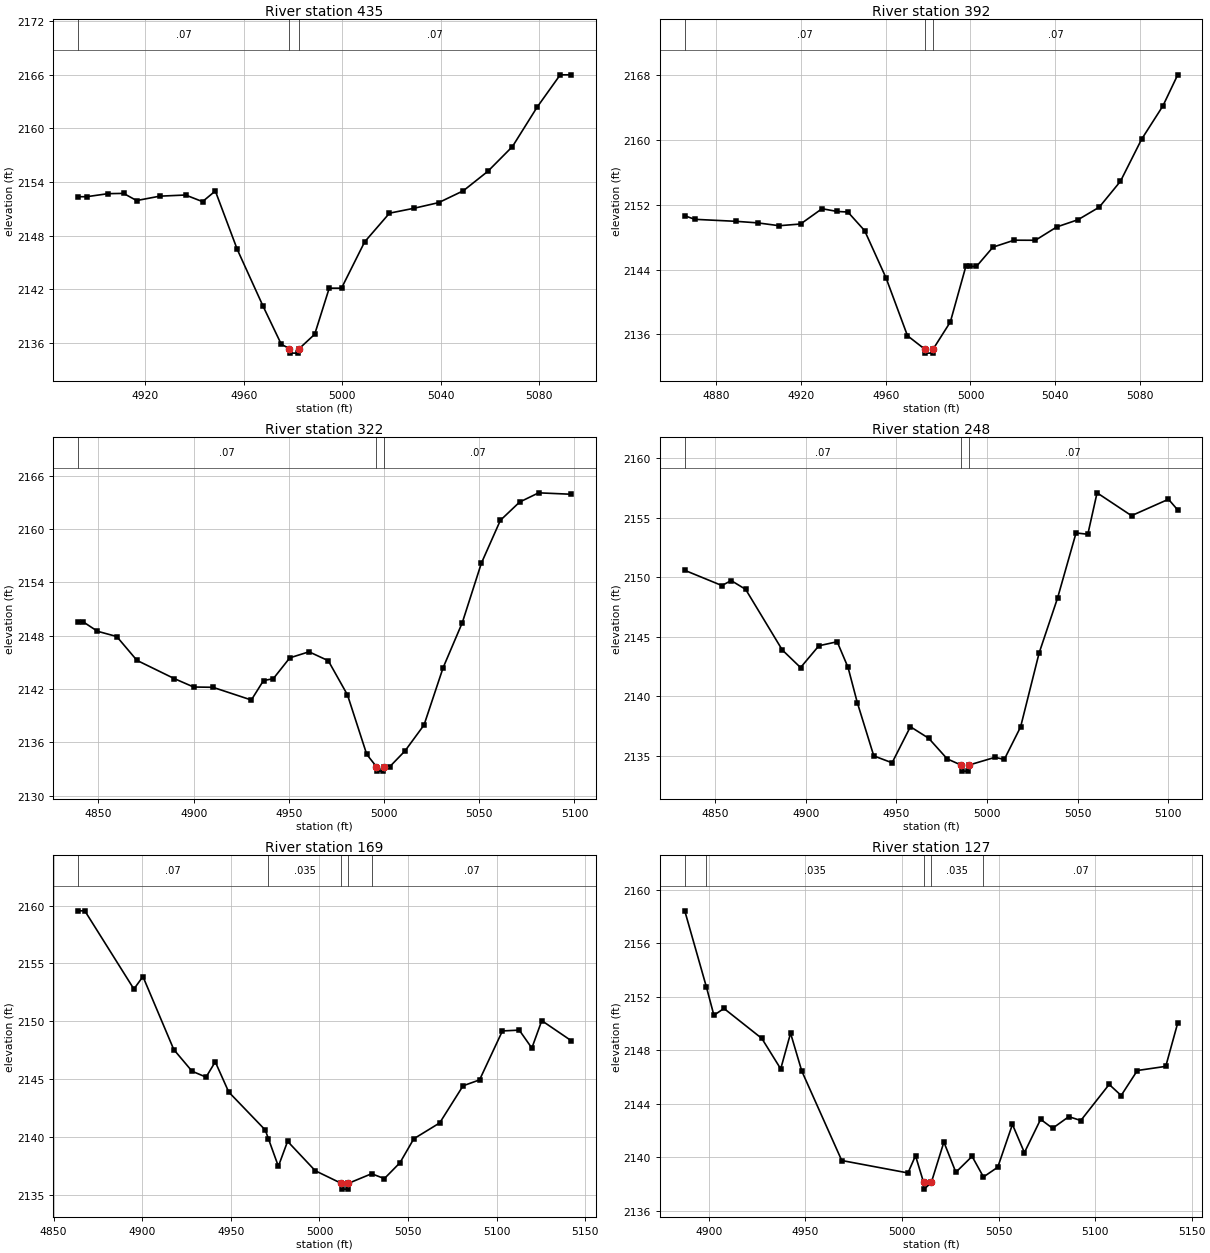
Type RM Length L Ch R = 1,435,43,43,43
BEGIN DESCRIPTION:
Elm 80 4056
END DESCRIPTION:
XS GIS Cut Line= 3
      1535953.42      6763326.97      1536051.16      6763358.49
      1536148.79      6763362.14
#Sta/Elev= 29
  4892.6 2152.35  4896.1 2152.35  4904.8 2152.69  4911.1 2152.72  4916.4 2151.92
  4925.8 2152.41  4936.3 2152.54  4943.2 2151.80  4948.4 2152.99  4957.3 2146.47
  4967.8 2140.12  4975.2 2135.87  4978.5 2135.37  4978.7 2134.87  4982.2 2134.87
  4982.5 2135.37  4988.8 2136.98  4994.7 2142.13  4999.7 2142.13  5009.1 2147.30
  5019.2 2150.51  5029.2 2151.06  5039.2 2151.69  5049.2 2153.01  5059.2 2155.19
  5069.2 2157.96  5079.2 2162.35  5088.6 2165.97  5093.0 2165.97
#Mann=3,-1,0
  4892.6    0.07       0  4978.5    0.07       0  4982.5    0.07       0
Bank Sta=4978.5,4982.5
Exp/Cntr=0.3,0.1

Type RM Length L Ch R = 1,392,70,70,70
BEGIN DESCRIPTION:
Elm 80 4055
END DESCRIPTION:
XS GIS Cut Line= 3
      1535920.94      6763382.98      1536054.40      6763401.20
      1536151.97      6763396.10
#Sta/Elev= 30
  4865.3 2150.66  4870.0 2150.22  4889.6 2149.97  4899.7 2149.78  4909.8 2149.43
  4919.9 2149.64  4930.0 2151.53  4937.2 2151.19  4942.2 2151.12  4950.1 2148.82
  4960.2 2142.97  4970.3 2135.83  4978.4 2134.18  4978.7 2133.68  4982.2 2133.68
  4982.4 2134.18  4990.5 2137.53  4997.8 2144.39  5000.0 2144.39  5002.8 2144.39
  5010.6 2146.78  5020.6 2147.64  5030.6 2147.63  5040.7 2149.28  5050.7 2150.17
  5060.7 2151.72  5070.7 2154.92  5080.7 2160.13  5090.7 2164.23  5097.7 2168.08
#Mann=3,-1,0
  4865.3    0.07       0  4978.4    0.07       0  4982.4    0.07       0
Bank Sta=4978.4,4982.4
Exp/Cntr=0.3,0.1

Type RM Length L Ch R = 1,322,74,74,74
BEGIN DESCRIPTION:
Elm 80 4054
END DESCRIPTION:
XS GIS Cut Line= 3
      1535894.88      6763449.38      1536054.05      6763471.52
      1536151.95      6763463.86
#Sta/Elev= 30
  4839.3 2149.58  4841.9 2149.58  4849.5 2148.51  4859.6 2147.92  4870.2 2145.24
  4889.9 2143.18  4900.0 2142.24  4910.1 2142.21  4930.3 2140.78  4936.7 2142.97
  4941.8 2143.17  4950.5 2145.52  4960.6 2146.20  4970.7 2145.20  4980.8 2141.35
  4990.9 2134.67  4996.0 2133.28  4996.2 2132.78  4999.7 2132.78  5000.0 2133.28
  5003.0 2133.28  5011.0 2135.05  5021.0 2137.97  5031.0 2144.40  5041.1 2149.48
  5051.1 2156.16  5061.1 2160.99  5071.2 2163.04  5081.2 2164.08  5098.2 2163.92
#Mann=3,-1,0
  4839.3    0.07       0  4996.0    0.07       0  5000.0    0.07       0
Bank Sta=4996,5000
Exp/Cntr=0.3,0.1

Type RM Length L Ch R = 1,248,79,79,79
BEGIN DESCRIPTION:
Elm 80 4053
END DESCRIPTION:
XS GIS Cut Line= 3
      1535881.80      6763519.69      1536046.81      6763544.08
      1536150.00      6763523.61
#Sta/Elev= 30
  4833.2 2150.59  4853.7 2149.31  4858.8 2149.73  4866.8 2148.99  4887.0 2143.90
  4897.1 2142.42  4907.2 2144.25  4917.3 2144.59  4923.3 2142.43  4928.4 2139.48
  4937.5 2135.00  4947.6 2134.42  4957.7 2137.45  4967.8 2136.48  4978.0 2134.75
  4985.8 2134.22  4986.1 2133.72  4989.6 2133.72  4989.8 2134.22  5004.4 2134.88
  5009.5 2134.70  5018.5 2137.43  5028.7 2143.63  5038.9 2148.26  5049.1 2153.73
  5055.6 2153.62  5060.7 2157.10  5079.7 2155.18  5100.1 2156.56  5105.2 2155.66
#Mann=3,-1,0
  4833.2    0.07       0  4985.8    0.07       0  4989.8    0.07       0
Bank Sta=4985.8,4989.8
Exp/Cntr=0.3,0.1

Type RM Length L Ch R = 1,169,42,42,42
BEGIN DESCRIPTION:
Elm 80 4052
END DESCRIPTION:
XS GIS Cut Line= 3
      1535872.69      6763574.37      1536004.62      6763608.20
      1536130.95      6763543.58
#Sta/Elev= 30
  4863.8 2159.55  4867.6 2159.55  4895.3 2152.79  4900.4 2153.87  4917.8 2147.56
  4928.1 2145.69  4936.0 2145.18  4941.2 2146.50  4948.8 2143.89  4969.4 2140.61
  4971.2 2139.85  4976.8 2137.47  4982.0 2139.63  4997.6 2137.09  5012.3 2136.00
  5012.6 2135.50  5016.1 2135.50  5016.3 2136.00  5029.4 2136.83  5036.6 2136.41
  5045.4 2137.78  5053.2 2139.85  5067.8 2141.22  5081.0 2144.43  5090.3 2144.94
  5103.2 2149.17  5112.7 2149.24  5119.8 2147.69  5125.4 2150.06  5141.9 2148.34
#Mann=5,-1,0
  4863.8    0.07       0  4971.2   0.035       0  5012.3   0.035       0
  5016.3   0.035       0  5029.4    0.07       0
Bank Sta=5012.3,5016.3
Exp/Cntr=0.3,0.1

Type RM Length L Ch R = 1,127,92,92,92
BEGIN DESCRIPTION:
Elm 80 4051
END DESCRIPTION:
XS GIS Cut Line= 3
      1535906.53      6763677.25      1536015.08      6763647.71
      1536130.03      6763562.98
#Sta/Elev= 30
  4887.5 2158.41  4898.7 2152.72  4902.6 2150.60  4907.8 2151.11  4927.4 2148.87
  4937.2 2146.59  4942.3 2149.26  4948.1 2146.43  4968.8 2139.74  5003.1 2138.81
  5007.0 2140.10  5011.2 2138.10  5011.5 2137.60  5015.2 2138.10  5021.7 2141.12
  5027.9 2138.86  5036.3 2140.05  5042.2 2138.51  5049.6 2139.24  5057.2 2142.44
  5063.4 2140.33  5071.8 2142.82  5078.0 2142.15  5086.4 2143.02  5092.6 2142.73
  5107.3 2145.43  5113.5 2144.60  5121.9 2146.47  5136.6 2146.78  5142.8 2150.02
#Mann=5,-1,0
  4887.5    0.07       0  4898.7   0.035       0  5011.2   0.035       0
  5015.2   0.035       0  5042.2    0.07       0
Bank Sta=5011.2,5015.2
Exp/Cntr=0.3,0.1

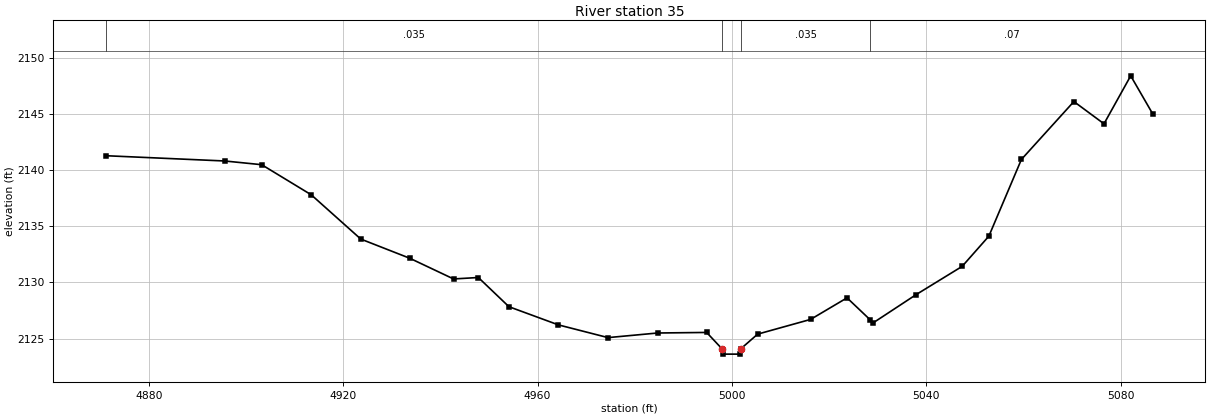
Type RM Length L Ch R = 1,35,0,0,0
BEGIN DESCRIPTION:
Elm 80 4050
END DESCRIPTION:
XS GIS Cut Line= 3
      1535953.46      6763737.13      1536080.00      6763713.00
      1536113.59      6763632.99
#Sta/Elev= 30
  4871.1 2141.27  4895.6 2140.80  4903.2 2140.47  4913.4 2137.79  4923.6 2133.85
  4933.7 2132.14  4942.7 2130.30  4947.8 2130.43  4954.1 2127.83  4964.3 2126.21
  4974.5 2125.08  4984.7 2125.49  4994.8 2125.54  4997.9 2124.11  4998.2 2123.61
  5001.7 2123.61  5001.9 2124.11  5005.3 2125.39  5016.2 2126.70  5023.7 2128.62
  5028.5 2126.65  5029.1 2126.40  5037.9 2128.90  5047.4 2131.42  5052.9 2134.11
  5059.6 2140.94  5070.4 2146.09  5076.6 2144.11  5082.1 2148.38  5086.7 2144.94
#Mann=4,-1,0
  4871.1   0.035       0  4997.9   0.035       0  5001.9   0.035       0
  5028.5    0.07       0
Bank Sta=4997.9,5001.9
Exp/Cntr=0.3,0.1

Chan Stop Cuts=-1