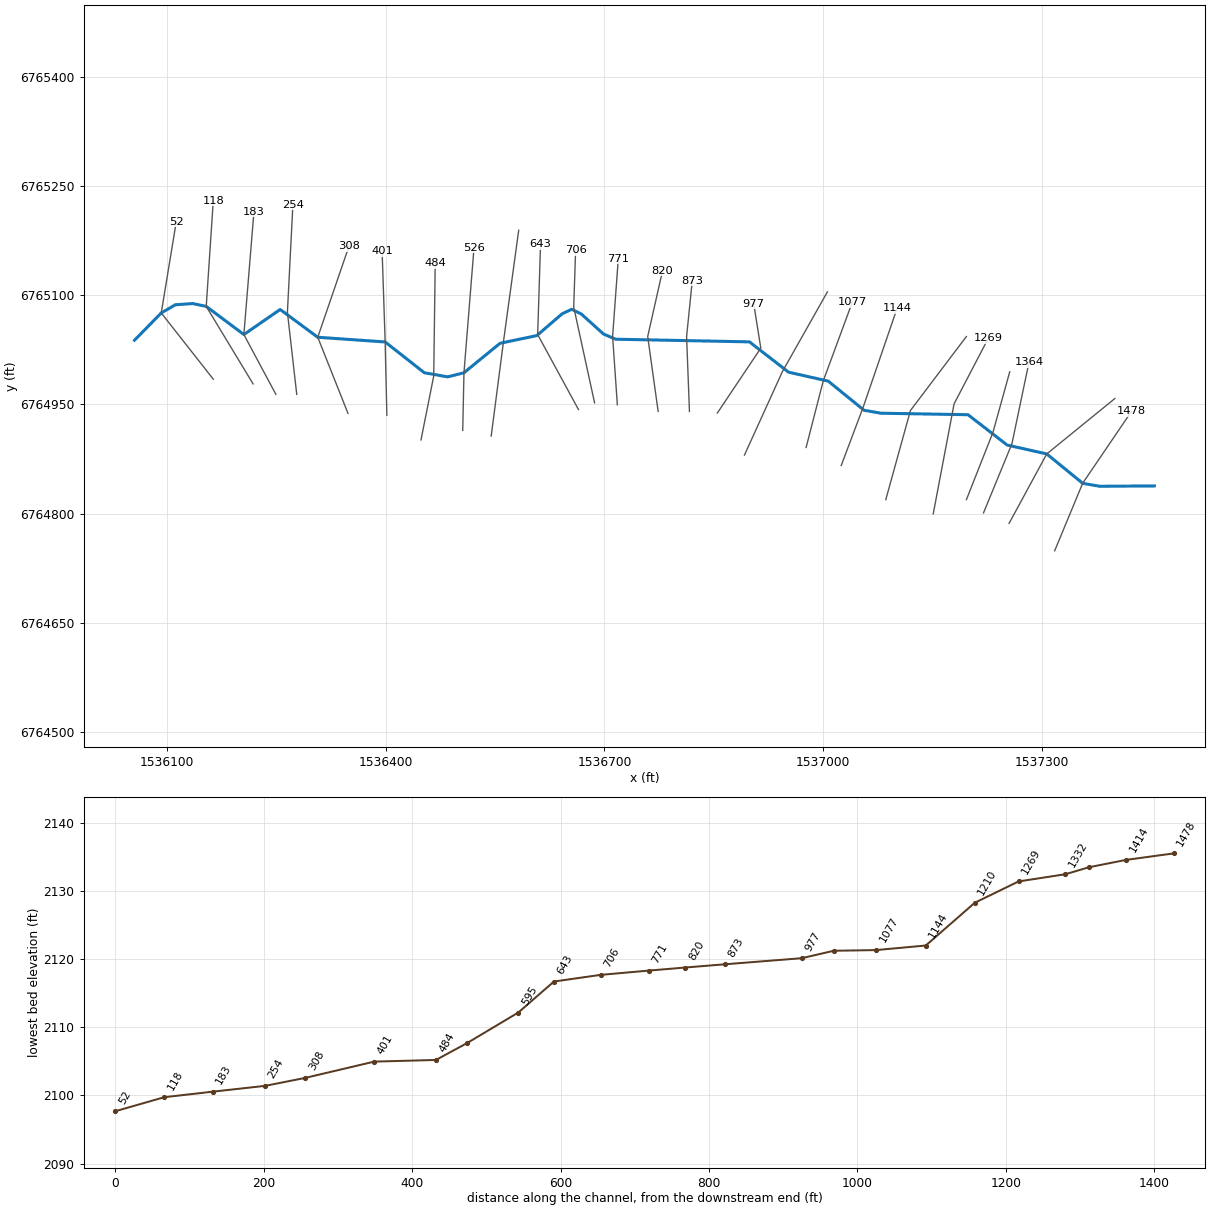
--- Elm 81.prj (project) ---

Proj Title=Elm 81 Base Level Engineering
Current Plan=p01
Default Exp/Contr=0.3,0.1
English Units
Geom File=g01
Flow File=f01
Plan File=p01
BEGIN DESCRIPTION:
Elm 81
END DESCRIPTION:

--- Elm 81.p01 (plan) ---

Plan Title=Multiple Run
Short Identifier=Multiple
Geom File=g01
Flow File=f01
Subcritical Flow
K Sum by GR= 0
Std Step Tol= 0.01
Critical Tol= 0.01
Num of Std Step Trials= 20
Max Error Tol= 0.3
Flow Tol Ratio= 0.001
Split Flow NTrial= 30
Split Flow Tol= 0.02
Split Flow Ratio= 0.02
Log Output Level= 0
Friction Slope Method= 1
Unsteady Friction Slope Method= 2
Unsteady Bridges Friction Slope Method= 1
Parabolic Critical Depth
Global Vel Dist=  1 , 1 , 1
Global Log Level= 0
CheckData=True
Encroach Param= -1, 0, 0, 0
BEGIN DESCRIPTION:
Multiple Run
END DESCRIPTION:

--- Elm 81.f01 (steady flow) ---

Flow Title=Multiple
Number of Profiles=7
Profile Names=10-year,25-year,50-year,1pct_min,100-year,1pct_plu,500-year
River Rch & RM= Elm 81,Reach-1,1478
     115     155     187     141     226     311     335
Boundary for River Rch & Prof#=Elm 81,Reach-1,1
Up Type=0
Dn Type=3
Dn Slope=0.005
Boundary for River Rch & Prof#=Elm 81,Reach-1,2
Up Type=0
Dn Type=3
Dn Slope=0.005
Boundary for River Rch & Prof#=Elm 81,Reach-1,3
Up Type=0
Dn Type=3
Dn Slope=0.005
Boundary for River Rch & Prof#=Elm 81,Reach-1,4
Up Type=0
Dn Type=3
Dn Slope=0.005
Boundary for River Rch & Prof#=Elm 81,Reach-1,5
Up Type=0
Dn Type=3
Dn Slope=0.005
Boundary for River Rch & Prof#=Elm 81,Reach-1,6
Up Type=0
Dn Type=3
Dn Slope=0.005
Boundary for River Rch & Prof#=Elm 81,Reach-1,7
Up Type=0
Dn Type=3
Dn Slope=0.005

--- Elm 81.g01 (geometry) ---

Geom Title=Existing Conditions

River Reach=Elm 81,Reach-1
Reach XY= 30
      1537455.00      6764838.00      1537379.80      6764837.52
      1537356.50      6764841.63      1537307.19      6764881.91
      1537252.82      6764894.12      1537199.07      6764935.75
      1537079.92      6764937.81      1537056.56      6764941.76
      1537007.18      6764981.88      1536952.82      6764994.12
      1536899.07      6765035.76      1536715.44      6765039.38
      1536698.81      6765046.46      1536668.20      6765074.06
      1536654.99      6765080.47      1536641.76      6765074.12
      1536607.29      6765044.39      1536556.74      6765033.81
      1536507.20      6764993.34      1536484.83      6764987.70
      1536452.82      6764993.37      1536399.03      6765035.62
      1536306.50      6765042.08      1536254.90      6765080.21
      1536205.08      6765045.80      1536153.42      6765084.42
      1536134.94      6765088.32      1536111.06      6765086.67
      1536091.66      6765075.44      1536055.00      6765038.00

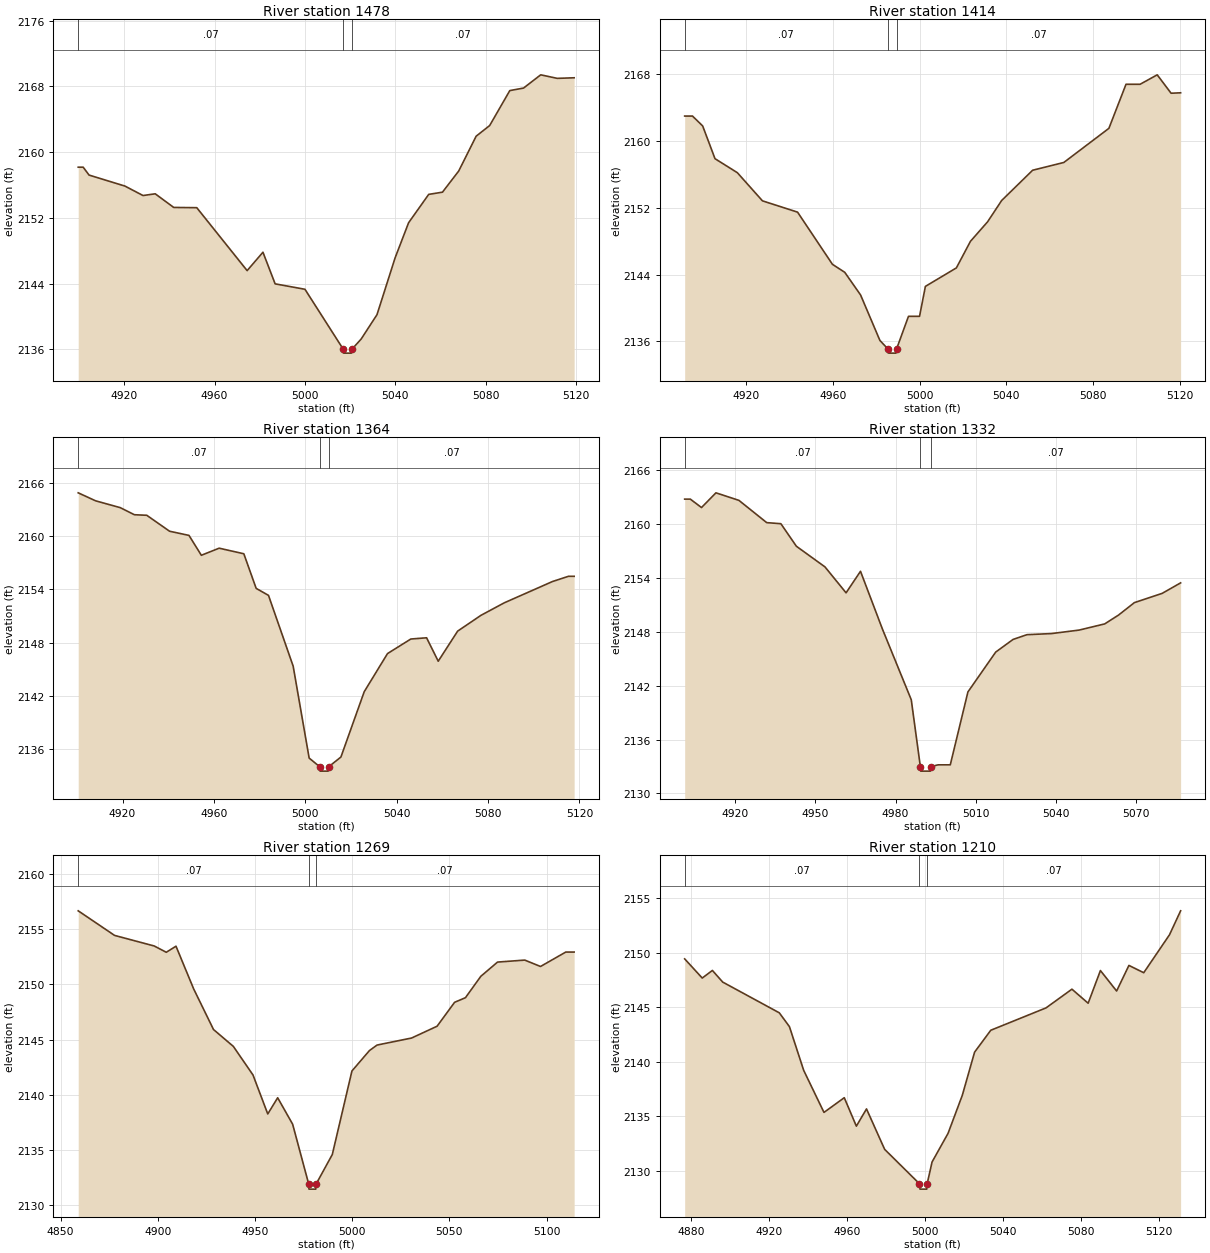
Type RM Length L Ch R = 1,1478,64,64,64
BEGIN DESCRIPTION:
Elm 81 4082
END DESCRIPTION:
XS GIS Cut Line= 3
      1537318.04      6764748.89      1537356.50      6764841.63
      1537423.48      6764940.24
#Sta/Elev= 30
  4899.6 2158.18  4901.8 2158.18  4904.4 2157.22  4920.3 2155.88  4928.3 2154.73
  4933.7 2154.94  4941.9 2153.28  4952.1 2153.25  4974.4 2145.59  4981.4 2147.83
  4986.8 2143.98  5000.0 2143.32  5016.9 2136.05  5017.1 2135.55  5020.6 2135.55
  5020.9 2136.05  5024.9 2137.27  5031.9 2140.23  5039.9 2147.13  5045.9 2151.42
  5054.8 2154.87  5060.9 2155.14  5068.1 2157.72  5075.8 2161.95  5081.8 2163.25
  5090.7 2167.50  5096.8 2167.81  5104.4 2169.42  5111.7 2168.99  5119.2 2169.06
#Mann=3,-1,0
  4899.6    0.07       0  5016.9    0.07       0  5020.9    0.07       0
Bank Sta=5016.9,5020.9
Exp/Cntr=0.3,0.1

Type RM Length L Ch R = 1,1414,50,50,50
BEGIN DESCRIPTION:
Elm 81 1414.157
END DESCRIPTION:
XS GIS Cut Line= 3
      1537255.53      6764786.62      1537307.19      6764881.91
      1537400.68      6764957.94
#Sta/Elev= 30
  4891.6 2162.95  4895.2 2162.95  4899.9 2161.77  4905.6 2157.85  4915.9 2156.18
  4927.5 2152.81  4943.7 2151.46  4959.8 2145.22  4965.5 2144.26  4972.8 2141.55
  4981.7 2136.12  4985.4 2135.10  4985.6 2134.60  4989.1 2134.60  4989.4 2135.10
  4994.9 2139.00  5000.0 2139.00  5002.7 2142.58  5017.0 2144.79  5023.5 2147.97
  5031.4 2150.30  5037.9 2152.85  5052.2 2156.47  5066.6 2157.40  5087.4 2161.48
  5095.3 2166.75  5101.8 2166.75  5109.7 2167.88  5116.1 2165.68  5120.5 2165.73
#Mann=3,-1,0
  4891.6    0.07       0  4985.4    0.07       0  4989.4    0.07       0
Bank Sta=4985.4,4989.4
Exp/Cntr=0.3,0.1

Type RM Length L Ch R = 1,1364,32,32,32
BEGIN DESCRIPTION:
Elm 81 1363.92
END DESCRIPTION:
XS GIS Cut Line= 3
      1537220.39      6764800.98      1537259.43      6764895.99
      1537282.86      6765007.94
#Sta/Elev= 30
  4900.6 2164.89  4908.2 2163.99  4919.0 2163.22  4925.2 2162.42  4930.6 2162.36
  4940.6 2160.56  4949.1 2160.09  4954.5 2157.85  4962.3 2158.65  4973.1 2158.02
  4978.5 2154.12  4983.9 2153.33  4994.7 2145.35  5001.7 2134.99  5006.3 2134.02
  5006.5 2133.52  5010.0 2133.52  5010.3 2134.02  5015.6 2135.11  5025.8 2142.47
  5036.0 2146.77  5046.2 2148.41  5053.1 2148.55  5058.2 2145.91  5066.7 2149.30
  5076.9 2151.08  5087.1 2152.49  5108.2 2154.89  5115.2 2155.48  5117.7 2155.48
#Mann=3,-1,0
  4900.6    0.07       0  5006.3    0.07       0  5010.3    0.07       0
Bank Sta=5006.3,5010.3
Exp/Cntr=0.3,0.1

Type RM Length L Ch R = 1,1332,63,63,63
BEGIN DESCRIPTION:
Elm 81 1332.46
END DESCRIPTION:
XS GIS Cut Line= 3
      1537196.92      6764819.13      1537233.39      6764911.62
      1537256.39      6764994.67
#Sta/Elev= 30
  4901.1 2162.79  4903.2 2162.79  4907.4 2161.85  4912.8 2163.49  4921.4 2162.65
  4931.8 2160.17  4937.1 2160.05  4942.9 2157.54  4953.6 2155.24  4961.5 2152.35
  4966.9 2154.75  4975.1 2148.32  4985.9 2140.44  4989.3 2132.99  4989.5 2132.49
  4993.0 2132.49  4993.3 2132.99  4995.9 2133.19  5000.5 2133.19  5007.1 2141.31
  5017.5 2145.75  5024.0 2147.16  5029.2 2147.69  5038.3 2147.81  5048.7 2148.20
  5058.3 2148.89  5063.5 2149.88  5069.4 2151.26  5079.8 2152.29  5086.7 2153.46
#Mann=3,-1,0
  4901.1    0.07       0  4989.3    0.07       0  4993.3    0.07       0
Bank Sta=4989.3,4993.3
Exp/Cntr=0.3,0.1

Type RM Length L Ch R = 1,1269,59,59,59
BEGIN DESCRIPTION:
Elm 81 1268.56
END DESCRIPTION:
XS GIS Cut Line= 3
      1537151.36      6764799.63      1537180.01      6764950.68
      1537226.89      6765040.54
#Sta/Elev= 30
  4859.1 2156.68  4877.8 2154.45  4898.2 2153.49  4904.4 2152.92  4909.4 2153.47
  4918.5 2149.59  4928.7 2145.91  4938.9 2144.38  4949.0 2141.79  4956.6 2138.25
  4961.7 2139.72  4969.4 2137.32  4977.6 2131.93  4977.8 2131.43  4981.3 2131.43
  4981.6 2131.93  4989.8 2134.57  4999.9 2142.15  5008.9 2144.00  5012.8 2144.50
  5030.6 2145.14  5043.7 2146.21  5052.7 2148.38  5058.3 2148.80  5066.2 2150.74
  5074.8 2152.03  5088.8 2152.21  5096.9 2151.63  5109.9 2152.94  5114.2 2152.94
#Mann=3,-1,0
  4859.1    0.07       0  4977.6    0.07       0  4981.6    0.07       0
Bank Sta=4977.6,4981.6
Exp/Cntr=0.3,0.1

Type RM Length L Ch R = 1,1210,66,66,66
BEGIN DESCRIPTION:
Elm 81 1210.07
END DESCRIPTION:
XS GIS Cut Line= 3
      1537086.26      6764819.19      1537120.11      6764941.56
      1537196.86      6765043.04
#Sta/Elev= 30
  4876.7 2149.43  4885.7 2147.67  4890.9 2148.37  4896.2 2147.30  4925.2 2144.48
  4930.4 2143.21  4937.7 2139.20  4948.1 2135.34  4958.5 2136.69  4964.7 2134.08
  4969.9 2135.66  4979.2 2131.95  4997.0 2128.80  4997.3 2128.30  5000.8 2128.30
  5001.0 2128.80  5003.5 2130.79  5011.7 2133.42  5019.0 2136.91  5025.3 2140.87
  5033.6 2142.88  5061.9 2144.93  5075.2 2146.65  5083.5 2145.36  5089.8 2148.36
  5098.1 2146.48  5104.4 2148.83  5112.0 2148.16  5125.2 2151.64  5130.9 2153.84
#Mann=3,-1,0
  4876.7    0.07       0  4997.0    0.07       0  5001.0    0.07       0
Bank Sta=4997,5001
Exp/Cntr=0.3,0.1

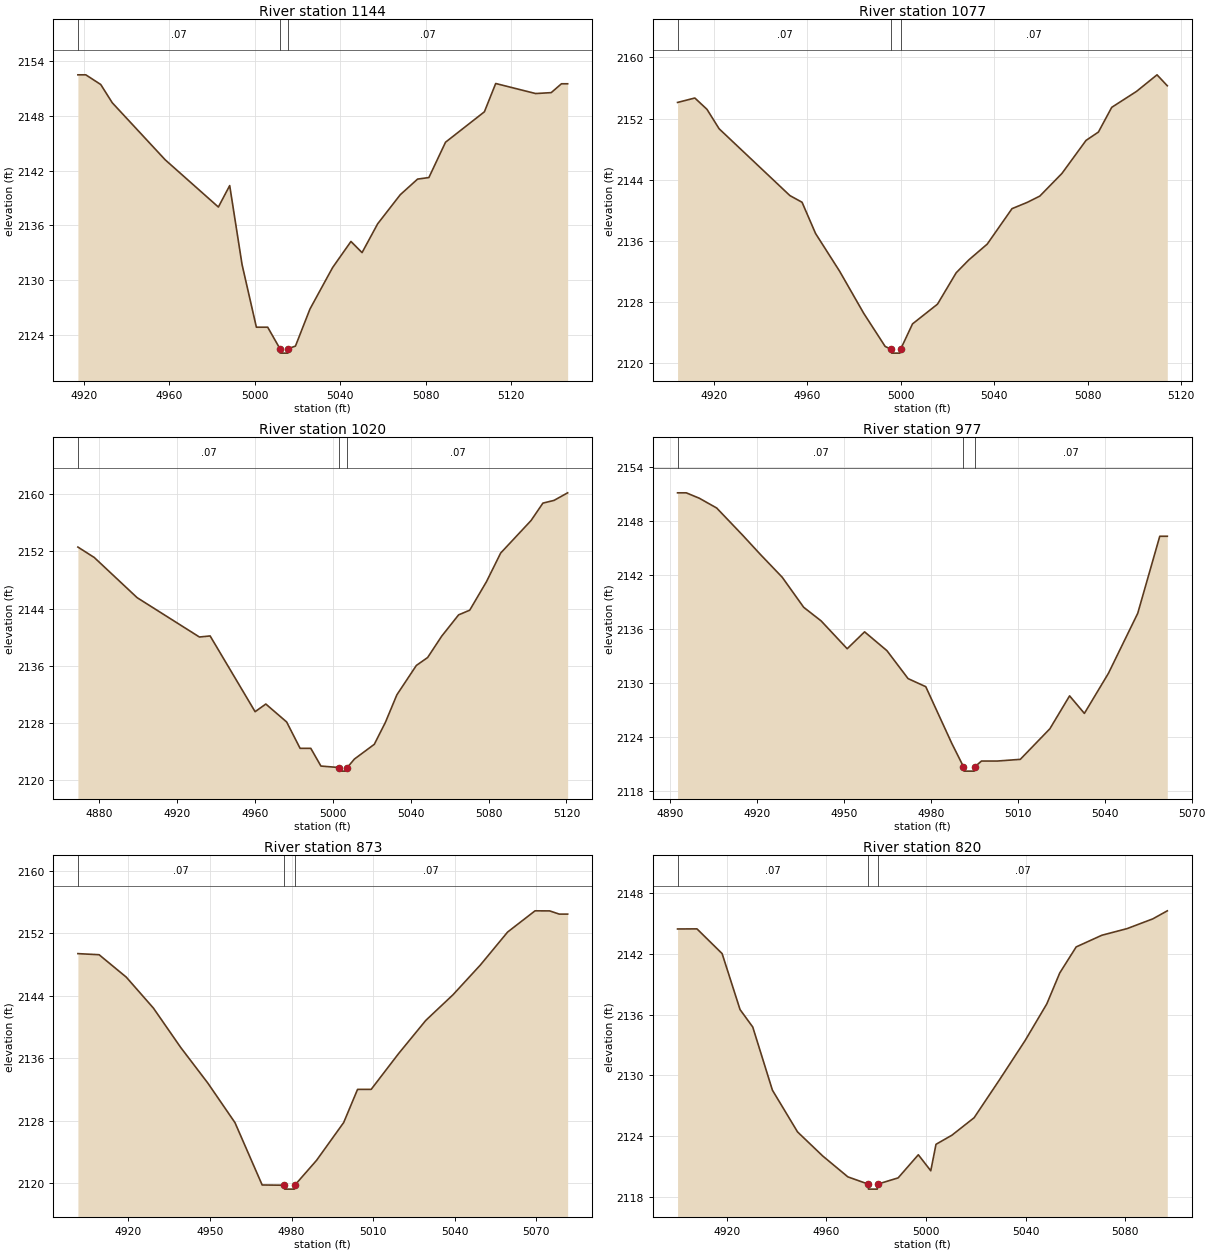
Type RM Length L Ch R = 1,1144,67,67,67
BEGIN DESCRIPTION:
Elm 81 1144.25
END DESCRIPTION:
XS GIS Cut Line= 3
      1537025.05      6764866.02      1537055.01      6764945.47
      1537101.87      6765082.15
#Sta/Elev= 30
  4917.1 2152.50  4920.8 2152.50  4927.8 2151.44  4933.2 2149.44  4958.0 2143.19
  4982.9 2138.02  4988.2 2140.37  4994.0 2131.71  5000.7 2124.86  5006.0 2124.86
  5011.7 2122.52  5011.9 2122.02  5015.4 2122.02  5015.7 2122.52  5019.0 2122.79
  5025.8 2126.85  5036.4 2131.39  5045.0 2134.25  5050.2 2133.03  5057.5 2136.18
  5068.1 2139.37  5076.2 2141.08  5081.5 2141.25  5089.3 2145.12  5107.5 2148.45
  5112.8 2151.55  5131.5 2150.45  5138.8 2150.55  5143.6 2151.52  5146.5 2151.52
#Mann=3,-1,0
  4917.1    0.07       0  5011.7    0.07       0  5015.7    0.07       0
Bank Sta=5011.7,5015.7
Exp/Cntr=0.3,0.1

Type RM Length L Ch R = 1,1077,57,57,57
BEGIN DESCRIPTION:
Elm 81 1077.03
END DESCRIPTION:
XS GIS Cut Line= 3
      1536976.88      6764890.77      1537000.32      6764981.93
      1537040.33      6765090.36
#Sta/Elev= 29
  4904.4 2154.11  4911.8 2154.69  4917.0 2153.21  4922.2 2150.67  4952.5 2141.94
  4957.7 2141.07  4963.5 2136.98  4973.8 2132.05  4984.1 2126.56  4993.3 2122.22
  4995.9 2121.85  4996.1 2121.35  4999.6 2121.35  4999.9 2121.85  5005.0 2125.17
  5015.7 2127.75  5023.7 2131.85  5029.1 2133.53  5037.0 2135.60  5047.6 2140.23
  5054.2 2141.06  5059.5 2141.87  5069.0 2144.84  5079.3 2149.15  5084.6 2150.24
  5090.3 2153.47  5100.9 2155.55  5109.7 2157.72  5114.1 2156.29
#Mann=3,-1,0
  4904.4    0.07       0  4995.9    0.07       0  4999.9    0.07       0
Bank Sta=4995.9,4999.9
Exp/Cntr=0.3,0.1

Type RM Length L Ch R = 1,1020,43,43,43
BEGIN DESCRIPTION:
Elm 81 1019.85
END DESCRIPTION:
XS GIS Cut Line= 3
      1536892.25      6764880.37      1536944.33      6764994.95
      1537006.11      6765104.35
#Sta/Elev= 30
  4869.1 2152.61  4877.5 2151.15  4899.5 2145.53  4931.5 2140.02  4937.0 2140.17
  4960.1 2129.57  4965.6 2130.64  4976.3 2128.13  4983.2 2124.44  4988.7 2124.44
  4993.9 2121.96  5003.4 2121.75  5003.6 2121.25  5007.1 2121.25  5007.4 2121.75
  5011.1 2122.94  5021.3 2125.00  5027.0 2128.07  5032.9 2131.93  5042.9 2136.04
  5048.7 2137.15  5055.9 2140.13  5064.6 2143.12  5070.3 2143.77  5078.9 2147.76
  5086.2 2151.77  5101.8 2156.32  5107.9 2158.76  5113.6 2159.14  5120.6 2160.20
#Mann=3,-1,0
  4869.1    0.07       0  5003.4    0.07       0  5007.4    0.07       0
Bank Sta=5003.4,5007.4
Exp/Cntr=0.3,0.1

Type RM Length L Ch R = 1,977,104,104,104
BEGIN DESCRIPTION:
Elm 81 977.316
END DESCRIPTION:
XS GIS Cut Line= 3
      1536855.01      6764938.02      1536914.67      6765027.20
      1536904.99      6765088.04
#Sta/Elev= 30
  4892.7 2151.11  4895.7 2151.11  4900.2 2150.51  4906.2 2149.42  4915.2 2146.38
  4921.2 2144.28  4928.8 2141.72  4936.2 2138.38  4942.2 2136.87  4951.2 2133.77
  4957.2 2135.65  4964.9 2133.56  4972.2 2130.45  4978.3 2129.55  4987.3 2123.23
  4991.3 2120.66  4991.5 2120.16  4995.0 2120.16  4995.3 2120.66  4997.5 2121.28
  5000.0 2121.28  5002.9 2121.28  5010.9 2121.47  5021.1 2124.87  5027.9 2128.53
  5033.0 2126.58  5041.3 2131.04  5051.4 2137.71  5059.0 2146.28  5061.6 2146.28
#Mann=3,-1,0
  4892.7    0.07       0  4991.3    0.07       0  4995.3    0.07       0
Bank Sta=4991.3,4995.3
Exp/Cntr=0.3,0.1

Type RM Length L Ch R = 1,873,53,53,53
BEGIN DESCRIPTION:
Elm 81 873.3
END DESCRIPTION:
XS GIS Cut Line= 3
      1536816.73      6764940.23      1536812.82      6765043.13
      1536820.63      6765119.96
#Sta/Elev= 25
  4901.4 2149.41  4909.2 2149.27  4919.2 2146.40  4929.2 2142.43  4939.2 2137.41
  4949.2 2132.84  4959.2 2127.77  4969.2 2119.79  4977.2 2119.76  4977.5 2119.26
  4981.0 2119.26  4981.2 2119.76  4989.2 2122.94  4999.2 2127.79  5004.3 2132.03
  5009.3 2132.03  5019.3 2136.57  5029.4 2140.86  5039.4 2144.14  5049.5 2147.96
  5059.5 2152.17  5069.6 2154.89  5075.0 2154.88  5078.5 2154.47  5081.6 2154.47
#Mann=3,-1,0
  4901.4    0.07       0  4977.2    0.07       0  4981.2    0.07       0
Bank Sta=4977.2,4981.2
Exp/Cntr=0.3,0.1

Type RM Length L Ch R = 1,820,49,49,49
BEGIN DESCRIPTION:
Elm 81 820.3
END DESCRIPTION:
XS GIS Cut Line= 3
      1536773.76      6764940.25      1536759.43      6765043.13
      1536779.84      6765133.69
#Sta/Elev= 28
  4900.2 2144.45  4908.0 2144.46  4918.1 2142.02  4925.3 2136.50  4930.4 2134.78
  4938.3 2128.55  4948.4 2124.43  4958.5 2122.06  4968.6 2120.00  4976.7 2119.29
  4976.9 2118.79  4980.4 2118.79  4980.7 2119.29  4988.8 2119.90  4996.9 2122.18
  5001.9 2120.60  5004.0 2123.21  5010.4 2124.11  5019.3 2125.83  5029.6 2129.61
  5039.8 2133.45  5048.5 2137.06  5053.7 2140.11  5060.3 2142.68  5070.6 2143.83
  5080.8 2144.49  5091.1 2145.45  5096.9 2146.24
#Mann=3,-1,0
  4900.2    0.07       0  4976.7    0.07       0  4980.7    0.07       0
Bank Sta=4976.7,4980.7
Exp/Cntr=0.3,0.1

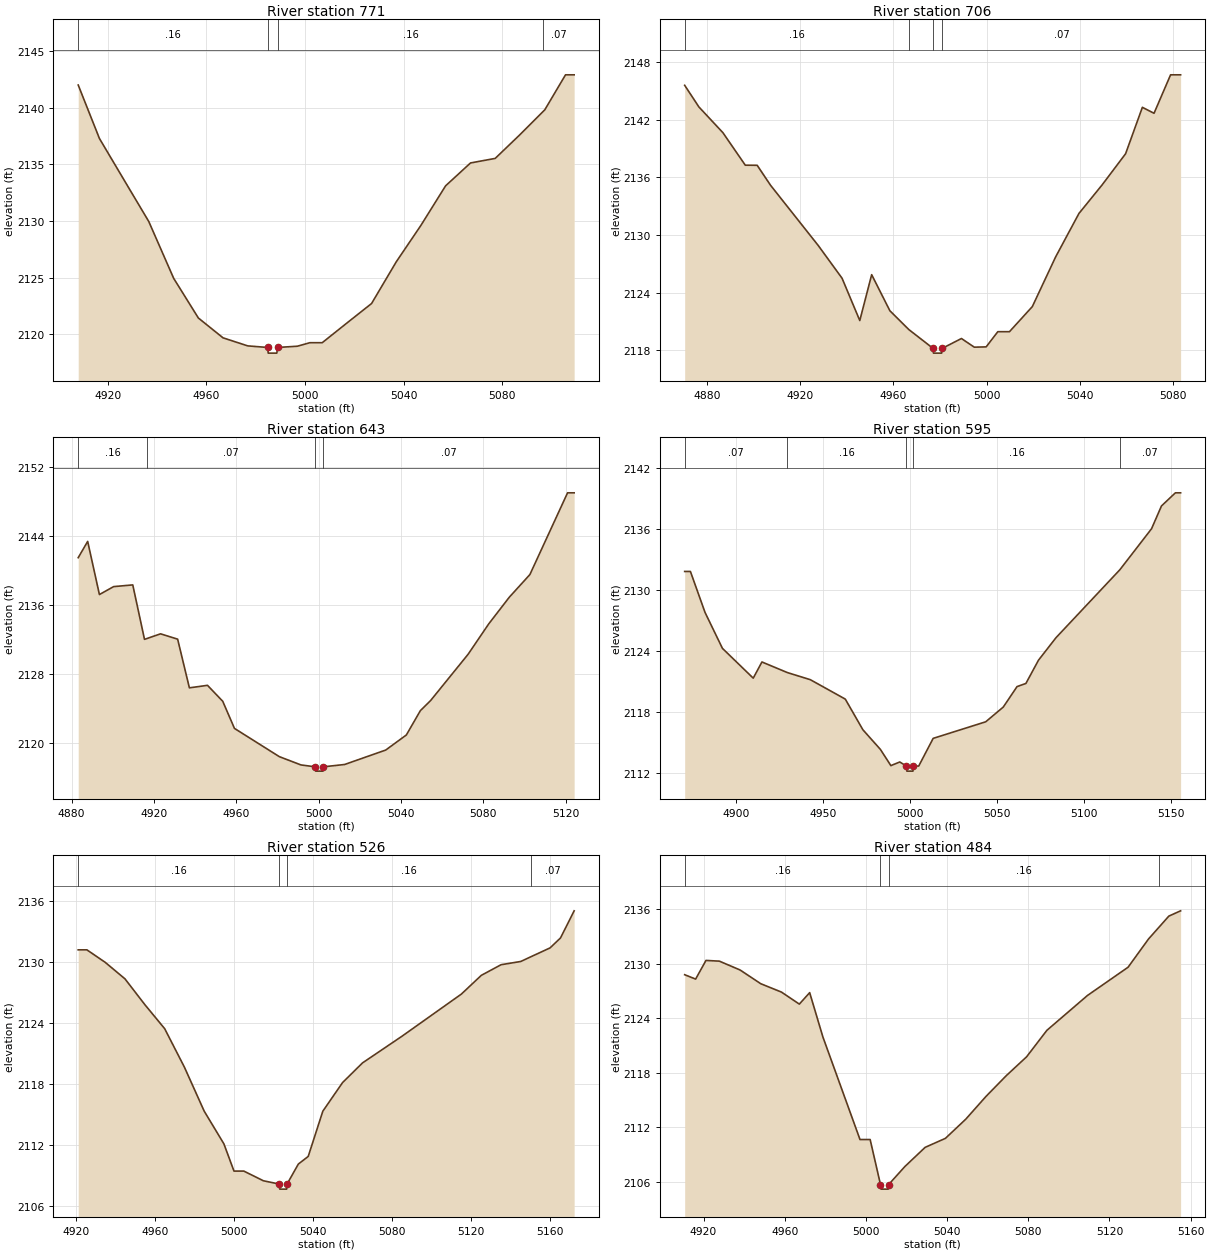
Type RM Length L Ch R = 1,771,65,65,65
BEGIN DESCRIPTION:
Elm 81 771.36
END DESCRIPTION:
XS GIS Cut Line= 3
      1536717.76      6764949.42      1536711.26      6765043.13
      1536719.07      6765149.91
#Sta/Elev= 27
  4908.1 2142.01  4916.7 2137.29  4926.7 2133.62  4936.7 2129.96  4946.8 2124.94
  4956.8 2121.44  4966.8 2119.69  4976.8 2118.98  4984.9 2118.84  4985.1 2118.34
  4988.6 2118.34  4988.9 2118.84  4996.9 2118.95  5002.0 2119.26  5007.0 2119.26
  5016.9 2120.98  5027.0 2122.72  5037.0 2126.40  5047.0 2129.62  5057.0 2133.11
  5067.1 2135.13  5077.1 2135.53  5087.1 2137.62  5096.6 2139.69  5097.2 2139.82
  5105.6 2142.91  5109.1 2142.91
#Mann=4,-1,0
  4908.1    0.16       0  4984.9    0.07       0  4988.9    0.16       0
  5096.6    0.07       0
Bank Sta=4984.9,4988.9
Exp/Cntr=0.3,0.1

Type RM Length L Ch R = 1,706,63,63,63
BEGIN DESCRIPTION:
Elm 81 706.18
END DESCRIPTION:
XS GIS Cut Line= 3
      1536686.51      6764952.02      1536657.87      6765083.49
      1536660.47      6765161.59
#Sta/Elev= 30
  4870.5 2145.57  4876.6 2143.32  4886.9 2140.64  4896.5 2137.26  4901.6 2137.25
  4907.3 2135.18  4927.8 2128.90  4938.0 2125.50  4945.6 2121.10  4950.7 2125.87
  4958.5 2122.12  4966.6 2120.17  4977.0 2118.21  4977.2 2117.71  4980.7 2117.71
  4981.0 2118.21  4989.2 2119.23  4994.7 2118.33  4999.8 2118.36  5004.8 2119.94
  5009.8 2119.94  5019.6 2122.55  5029.6 2127.72  5039.6 2132.24  5049.6 2135.23
  5059.6 2138.45  5066.8 2143.28  5071.8 2142.66  5078.9 2146.66  5083.2 2146.66
#Mann=4,-1,0
  4870.5    0.16       0  4966.6    0.07       0  4977.0    0.07       0
  4981.0    0.07       0
Bank Sta=4977,4981
Exp/Cntr=0.3,0.1

Type RM Length L Ch R = 1,643,48,48,48
BEGIN DESCRIPTION:
Elm 81 643.23
END DESCRIPTION:
XS GIS Cut Line= 3
      1536664.38      6764942.87      1536608.39      6765045.73
      1536612.30      6765169.46
#Sta/Elev= 30
  4883.2 2141.51  4887.8 2143.40  4893.5 2137.23  4900.4 2138.15  4909.7 2138.35
  4915.4 2132.03  4916.4 2132.11  4923.2 2132.67  4931.5 2132.05  4937.2 2126.40
  4946.0 2126.69  4953.4 2124.84  4959.1 2121.69  4980.9 2118.41  4991.4 2117.45
  4998.3 2117.23  4998.6 2116.73  5002.1 2116.73  5002.3 2117.23  5012.6 2117.50
  5032.6 2119.18  5042.6 2120.93  5049.4 2123.75  5054.4 2124.93  5072.6 2130.30
  5082.6 2133.82  5092.6 2136.92  5102.6 2139.55  5120.9 2149.04  5124.1 2149.04
#Mann=4,-1,0
  4883.2    0.16       0  4916.4    0.07       0  4998.3    0.07       0
  5002.3    0.07       0
Bank Sta=4998.3,5002.3
Exp/Cntr=0.3,0.1

Type RM Length L Ch R = 1,595,69,69,69
BEGIN DESCRIPTION:
Elm 81 594.57
END DESCRIPTION:
XS GIS Cut Line= 3
      1536544.59      6764906.44      1536561.52      6765036.62
      1536582.35      6765188.93
#Sta/Elev= 30
  4870.6 2131.81  4873.9 2131.81  4882.3 2127.78  4892.3 2124.25  4910.0 2121.32
  4915.0 2122.91  4929.6 2121.87  4942.8 2121.17  4962.9 2119.26  4973.0 2116.25
  4983.1 2114.31  4989.1 2112.72  4994.2 2113.08  4998.0 2112.68  4998.3 2112.18
  5001.8 2112.18  5002.0 2112.68  5005.1 2112.68  5013.4 2115.40  5043.6 2117.03
  5053.7 2118.48  5061.6 2120.49  5066.7 2120.80  5073.9 2123.08  5084.0 2125.30
  5120.7 2131.98  5138.9 2136.01  5144.6 2138.25  5152.6 2139.54  5155.6 2139.54
#Mann=5,-1,0
  4870.6    0.07       0  4929.6    0.16       0  4998.0    0.07       0
  5002.0    0.16       0  5120.7    0.07       0
Bank Sta=4998,5002
Exp/Cntr=0.3,0.1

Type RM Length L Ch R = 1,526,42,42,42
BEGIN DESCRIPTION:
Elm 81 525.961
END DESCRIPTION:
XS GIS Cut Line= 3
      1536505.53      6764914.26      1536507.20      6764993.34
      1536521.00      6765164.89
#Sta/Elev= 30
  4920.9 2131.18  4925.3 2131.18  4934.6 2129.95  4944.6 2128.33  4954.7 2125.79
  4964.7 2123.44  4974.7 2119.66  4984.7 2115.35  4994.7 2112.13  4999.8 2109.46
  5004.8 2109.46  5014.7 2108.51  5022.7 2108.19  5023.0 2107.69  5026.5 2107.69
  5026.7 2108.19  5032.4 2110.15  5037.4 2110.90  5044.8 2115.34  5054.8 2118.15
  5064.9 2120.08  5084.9 2122.70  5115.0 2126.84  5125.1 2128.68  5135.1 2129.72
  5145.1 2130.04  5150.4 2130.52  5159.9 2131.37  5165.2 2132.35  5172.1 2135.01
#Mann=4,-1,0
  4920.9    0.16       0  5022.7    0.07       0  5026.7    0.16       0
  5150.4    0.07       0
Bank Sta=5022.7,5026.7
Exp/Cntr=0.3,0.1

Type RM Length L Ch R = 1,484,83,83,83
BEGIN DESCRIPTION:
Elm 81 4066
END DESCRIPTION:
XS GIS Cut Line= 3
      1536448.23      6764901.19      1536465.69      6764988.76
      1536467.76      6765143.85
#Sta/Elev= 30
  4910.7 2128.77  4916.1 2128.29  4921.2 2130.34  4927.8 2130.26  4938.0 2129.29
  4948.2 2127.78  4958.4 2126.86  4967.2 2125.54  4972.3 2126.80  4978.8 2121.94
  4997.1 2110.66  5002.1 2110.66  5007.2 2105.71  5007.5 2105.21  5011.0 2105.21
  5011.2 2105.71  5019.2 2107.69  5029.2 2109.80  5039.2 2110.79  5049.2 2112.89
  5059.2 2115.40  5069.2 2117.68  5079.2 2119.75  5089.2 2122.66  5109.2 2126.49
  5129.2 2129.59  5139.3 2132.70  5144.6 2134.03  5149.3 2135.21  5155.1 2135.79
#Mann=4,-1,0
  4910.7    0.16       0  5007.2    0.07       0  5011.2    0.16       0
  5144.6    0.07       0
Bank Sta=5007.2,5011.2
Exp/Cntr=0.3,0.1

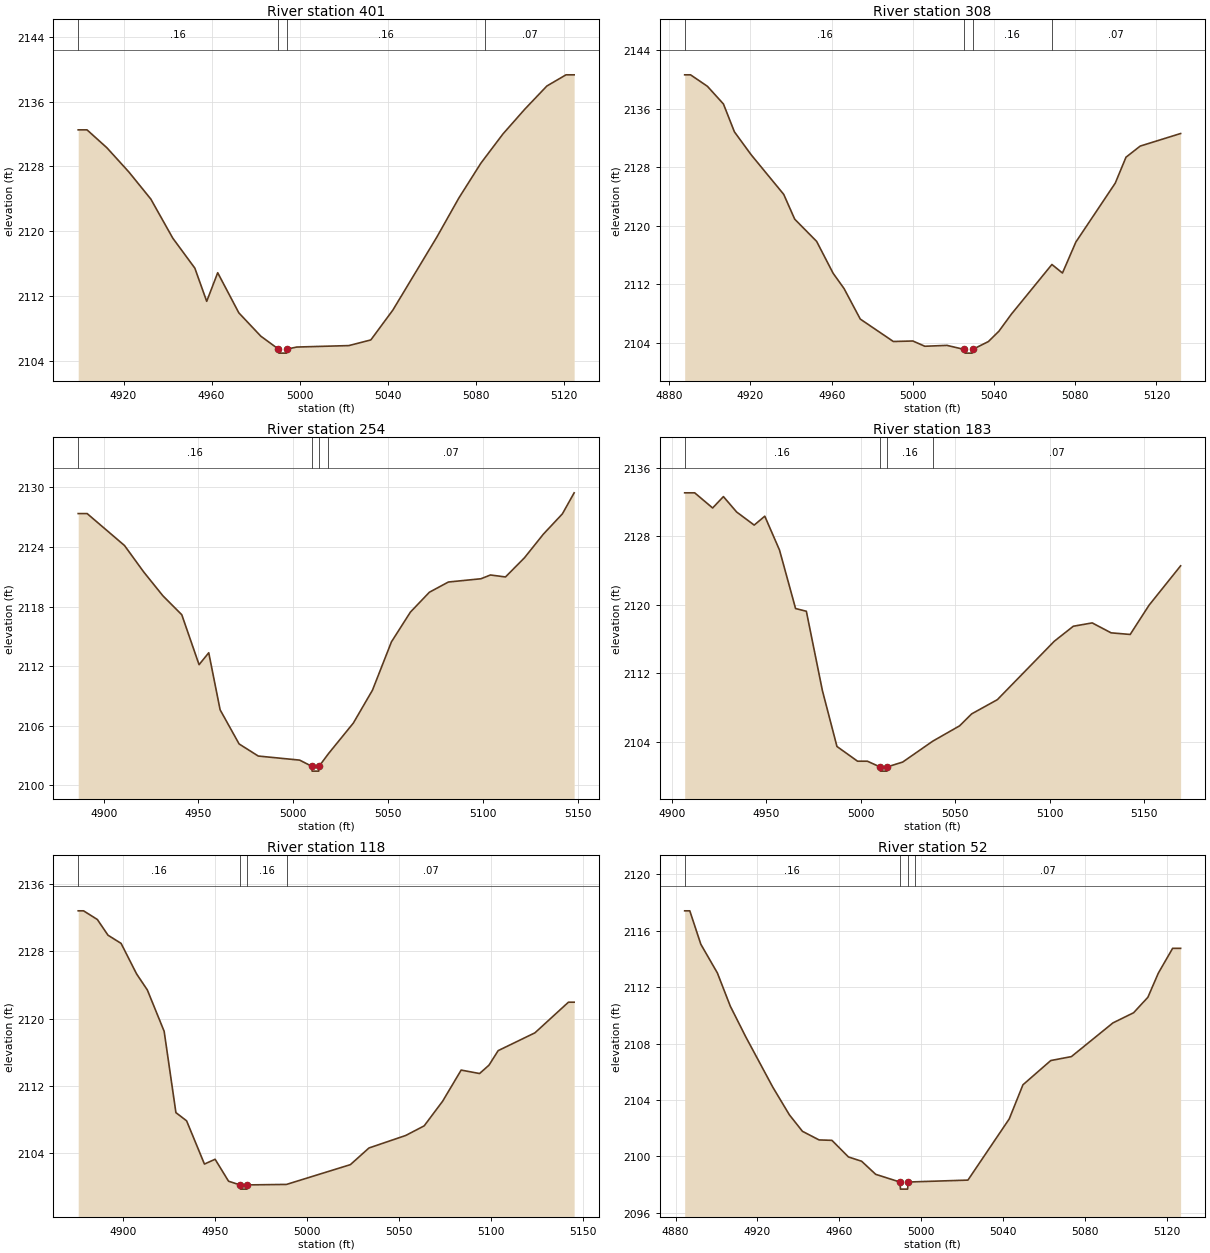
Type RM Length L Ch R = 1,401,93,93,93
BEGIN DESCRIPTION:
Elm 81 4065
END DESCRIPTION:
XS GIS Cut Line= 3
      1536401.36      6764935.05      1536399.03      6765035.62
      1536394.85      6765160.35
#Sta/Elev= 28
  4899.4 2132.52  4903.4 2132.52  4912.4 2130.32  4922.4 2127.33  4932.4 2123.98
  4942.4 2119.15  4952.4 2115.46  4957.8 2111.36  4962.8 2114.89  4972.4 2109.94
  4982.4 2107.06  4990.4 2105.47  4990.6 2104.97  4994.1 2104.97  4994.4 2105.47
  4998.7 2105.72  5022.4 2105.90  5032.4 2106.60  5042.4 2110.28  5062.4 2119.29
  5072.4 2124.11  5082.4 2128.40  5084.2 2129.05  5092.4 2132.00  5102.4 2135.08
  5112.4 2137.93  5121.1 2139.31  5124.8 2139.31
#Mann=4,-1,0
  4899.4    0.16       0  4990.4    0.07       0  4994.4    0.16       0
  5084.2    0.07       0
Bank Sta=4990.4,4994.4
Exp/Cntr=0.3,0.1

Type RM Length L Ch R = 1,308,54,54,54
BEGIN DESCRIPTION:
Elm 81 4064
END DESCRIPTION:
XS GIS Cut Line= 3
      1536347.99      6764937.62      1536306.50      6765042.08
      1536349.28      6765166.84
#Sta/Elev= 30
  4887.6 2140.66  4890.5 2140.66  4898.8 2139.09  4906.7 2136.67  4912.1 2132.86
  4920.3 2129.74  4936.4 2124.30  4941.8 2120.91  4952.6 2117.87  4960.7 2113.52
  4966.1 2111.42  4974.1 2107.24  4990.4 2104.17  5000.0 2104.24  5005.9 2103.52
  5016.8 2103.64  5025.4 2103.08  5025.7 2102.58  5029.2 2102.58  5029.4 2103.08
  5037.2 2104.16  5042.4 2105.58  5048.5 2107.90  5068.5 2114.71  5073.7 2113.54
  5080.3 2117.78  5099.7 2125.84  5105.0 2129.39  5112.0 2130.91  5131.9 2132.63
#Mann=4,-1,0
  4887.6    0.16       0  5025.4    0.07       0  5029.4    0.16       0
  5068.5    0.07       0
Bank Sta=5025.4,5029.4
Exp/Cntr=0.3,0.1

Type RM Length L Ch R = 1,254,71,71,71
BEGIN DESCRIPTION:
Elm 81 4063
END DESCRIPTION:
XS GIS Cut Line= 3
      1536277.66      6764963.72      1536264.85      6765076.39
      1536272.39      6765224.20
#Sta/Elev= 30
  4886.6 2127.37  4891.3 2127.37  4911.0 2124.15  4921.1 2121.49  4931.2 2119.09
  4941.2 2117.17  4950.3 2112.14  4955.4 2113.34  4961.4 2107.59  4971.4 2104.15
  4981.5 2102.93  5003.3 2102.52  5009.6 2101.91  5009.9 2101.41  5013.4 2101.41
  5013.6 2101.91  5018.5 2103.17  5031.6 2106.25  5041.7 2109.57  5051.7 2114.44
  5061.7 2117.44  5071.7 2119.44  5081.7 2120.47  5098.9 2120.80  5103.9 2121.18
  5111.8 2120.98  5121.8 2122.91  5131.8 2125.30  5141.8 2127.34  5148.0 2129.46
#Mann=4,-1,0
  4886.6    0.16       0  5009.6    0.07       0  5013.6    0.16       0
  5018.5    0.07       0
Bank Sta=5009.6,5013.6
Exp/Cntr=0.3,0.1

Type RM Length L Ch R = 1,183,65,65,65
BEGIN DESCRIPTION:
Elm 81 4062
END DESCRIPTION:
XS GIS Cut Line= 3
      1536249.01      6764963.72      1536205.08      6765045.80
      1536218.93      6765214.64
#Sta/Elev= 30
  4906.9 2133.07  4912.2 2133.07  4921.7 2131.30  4927.4 2132.63  4934.4 2130.83
  4943.7 2129.30  4949.3 2130.34  4957.1 2126.38  4965.6 2119.55  4971.3 2119.23
  4979.8 2109.96  4987.5 2103.43  4998.4 2101.71  5003.6 2101.71  5010.2 2101.05
  5010.5 2100.55  5014.0 2100.55  5014.2 2101.05  5022.3 2101.61  5038.2 2104.05
  5052.4 2105.84  5058.8 2107.24  5072.4 2108.90  5102.5 2115.72  5112.6 2117.48
  5122.6 2117.87  5132.6 2116.71  5142.7 2116.52  5152.7 2119.94  5169.4 2124.54
#Mann=4,-1,0
  4906.9    0.16       0  5010.2    0.07       0  5014.2    0.16       0
  5038.2    0.07       0
Bank Sta=5010.2,5014.2
Exp/Cntr=0.3,0.1

Type RM Length L Ch R = 1,118,66,66,66
BEGIN DESCRIPTION:
Elm 81 4061
END DESCRIPTION:
XS GIS Cut Line= 3
      1536217.75      6764978.05      1536153.42      6765084.42
      1536163.08      6765229.29
#Sta/Elev= 30
  4875.7 2132.82  4878.6 2132.82  4886.1 2131.79  4891.9 2129.92  4899.0 2128.95
  4907.4 2125.33  4913.3 2123.40  4922.4 2118.50  4928.8 2108.83  4934.6 2107.86
  4944.3 2102.72  4950.1 2103.29  4957.4 2100.68  4963.6 2100.24  4963.9 2099.74
  4967.4 2099.74  4967.6 2100.24  4988.9 2100.30  5023.6 2102.65  5033.7 2104.63
  5053.7 2106.12  5063.7 2107.26  5073.7 2110.18  5083.8 2113.89  5093.8 2113.48
  5098.9 2114.47  5103.9 2116.20  5123.9 2118.32  5142.1 2121.96  5145.2 2121.96
#Mann=4,-1,0
  4875.7    0.16       0  4963.6    0.07       0  4967.6    0.16       0
  4988.9    0.07       0
Bank Sta=4963.6,4967.6
Exp/Cntr=0.3,0.1

Type RM Length L Ch R = 1,52,0,0,0
BEGIN DESCRIPTION:
Elm 81 4060
END DESCRIPTION:
XS GIS Cut Line= 3
      1536163.08      6764984.54      1536091.66      6765075.44
      1536112.29      6765200.65
#Sta/Elev= 30
  4884.4 2117.42  4886.9 2117.42  4892.3 2115.05  4900.4 2113.01  4906.7 2110.66
  4914.2 2108.50  4927.5 2104.91  4935.6 2102.95  4942.0 2101.78  4950.1 2101.17
  4956.4 2101.14  4964.5 2099.96  4970.9 2099.66  4977.8 2098.73  4989.7 2098.18
  4989.9 2097.68  4993.4 2097.68  4993.7 2098.18  4997.1 2098.20  5022.9 2098.32
  5043.1 2102.66  5049.8 2105.08  5063.4 2106.80  5073.5 2107.08  5093.8 2109.47
  5103.9 2110.19  5110.9 2111.29  5116.0 2113.00  5123.0 2114.76  5126.9 2114.76
#Mann=4,-1,0
  4884.4    0.16       0  4989.7    0.07       0  4993.7    0.16       0
  4997.1    0.07       0
Bank Sta=4989.7,4993.7
Exp/Cntr=0.3,0.1

Chan Stop Cuts=-1