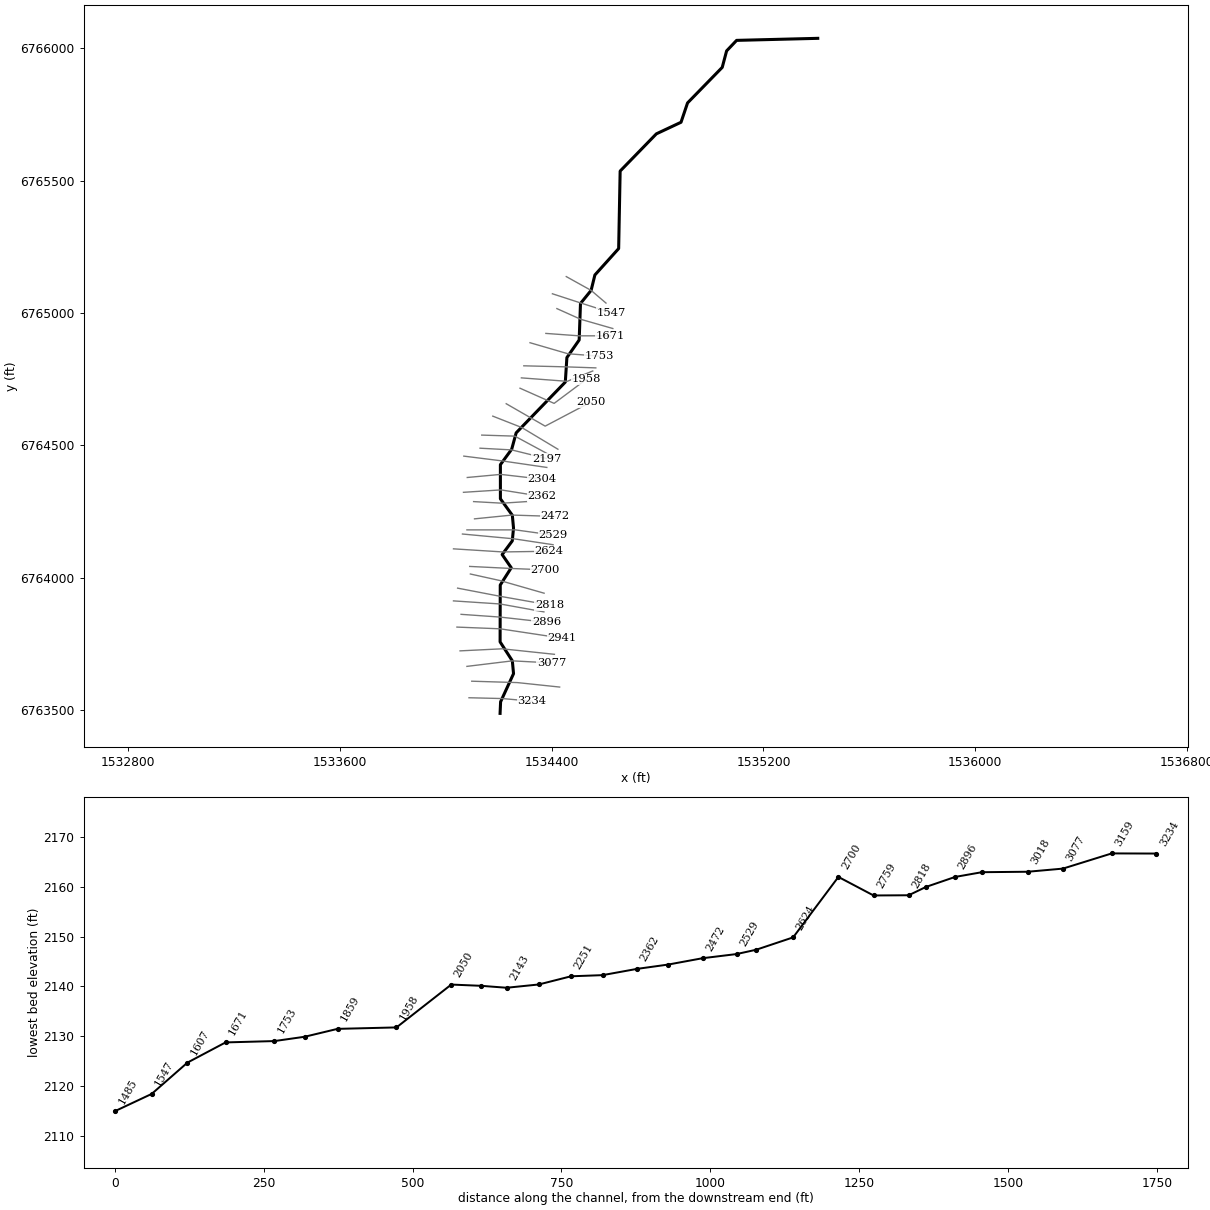
--- Elm 82.prj (project) ---

Proj Title=Elm 82 Base Level Engineering
Current Plan=p01
Default Exp/Contr=0.3,0.1
English Units
Geom File=g01
Flow File=f01
Plan File=p01
BEGIN DESCRIPTION:
Elm 82
END DESCRIPTION:

--- Elm 82.p01 (plan) ---

Plan Title=Multiple Run
Short Identifier=Multiple
Geom File=g01
Flow File=f01
Subcritical Flow
K Sum by GR= 0
Std Step Tol= 0.01
Critical Tol= 0.01
Num of Std Step Trials= 20
Max Error Tol= 0.3
Flow Tol Ratio= 0.001
Split Flow NTrial= 30
Split Flow Tol= 0.02
Split Flow Ratio= 0.02
Log Output Level= 0
Friction Slope Method= 1
Unsteady Friction Slope Method= 2
Unsteady Bridges Friction Slope Method= 1
Parabolic Critical Depth
Global Vel Dist=  1 , 1 , 1
Global Log Level= 0
CheckData=True
Encroach Param= -1, 0, 0, 0
BEGIN DESCRIPTION:
Multiple Run
END DESCRIPTION:

--- Elm 82.f01 (steady flow) ---

Flow Title=Multiple
Number of Profiles=7
Profile Names=10-year,25-year,50-year,1pct_min,100-year,1pct_plu,500-year
River Rch & RM= Elm 82,Reach-1,3234
     119     161     194     146     235     323     346
Boundary for River Rch & Prof#=Elm 82,Reach-1,1
Up Type=0
Dn Type=3
Dn Slope=0.005
Boundary for River Rch & Prof#=Elm 82,Reach-1,2
Up Type=0
Dn Type=3
Dn Slope=0.005
Boundary for River Rch & Prof#=Elm 82,Reach-1,3
Up Type=0
Dn Type=3
Dn Slope=0.005
Boundary for River Rch & Prof#=Elm 82,Reach-1,4
Up Type=0
Dn Type=3
Dn Slope=0.005
Boundary for River Rch & Prof#=Elm 82,Reach-1,5
Up Type=0
Dn Type=3
Dn Slope=0.005
Boundary for River Rch & Prof#=Elm 82,Reach-1,6
Up Type=0
Dn Type=3
Dn Slope=0.005
Boundary for River Rch & Prof#=Elm 82,Reach-1,7
Up Type=0
Dn Type=3
Dn Slope=0.005

--- Elm 82.g01 (geometry) ---

Geom Title=Existing Conditions

River Reach=Elm 82,Reach-1
Reach XY= 30
      1534205.00      6763488.00      1534206.99      6763531.73
      1534255.83      6763638.00      1534251.30      6763686.40
      1534205.07      6763758.03      1534205.65      6763972.84
      1534247.21      6764038.10      1534212.80      6764087.90
      1534251.07      6764139.50      1534255.79      6764187.99
      1534251.29      6764236.40      1534206.21      6764298.51
      1534206.19      6764427.50      1534248.86      6764485.83
      1534265.76      6764547.68      1534451.39      6764739.50
      1534457.36      6764832.02      1534503.77      6764898.51
      1534508.76      6765036.44      1534548.86      6765085.83
      1534563.16      6765144.05      1534652.94      6765243.86
      1534658.54      6765536.54      1534795.34      6765677.21
      1534888.50      6765720.95      1534913.17      6765794.03
      1535044.21      6765928.34      1535060.74      6765990.58
      1535098.52      6766030.31      1535405.00      6766038.00

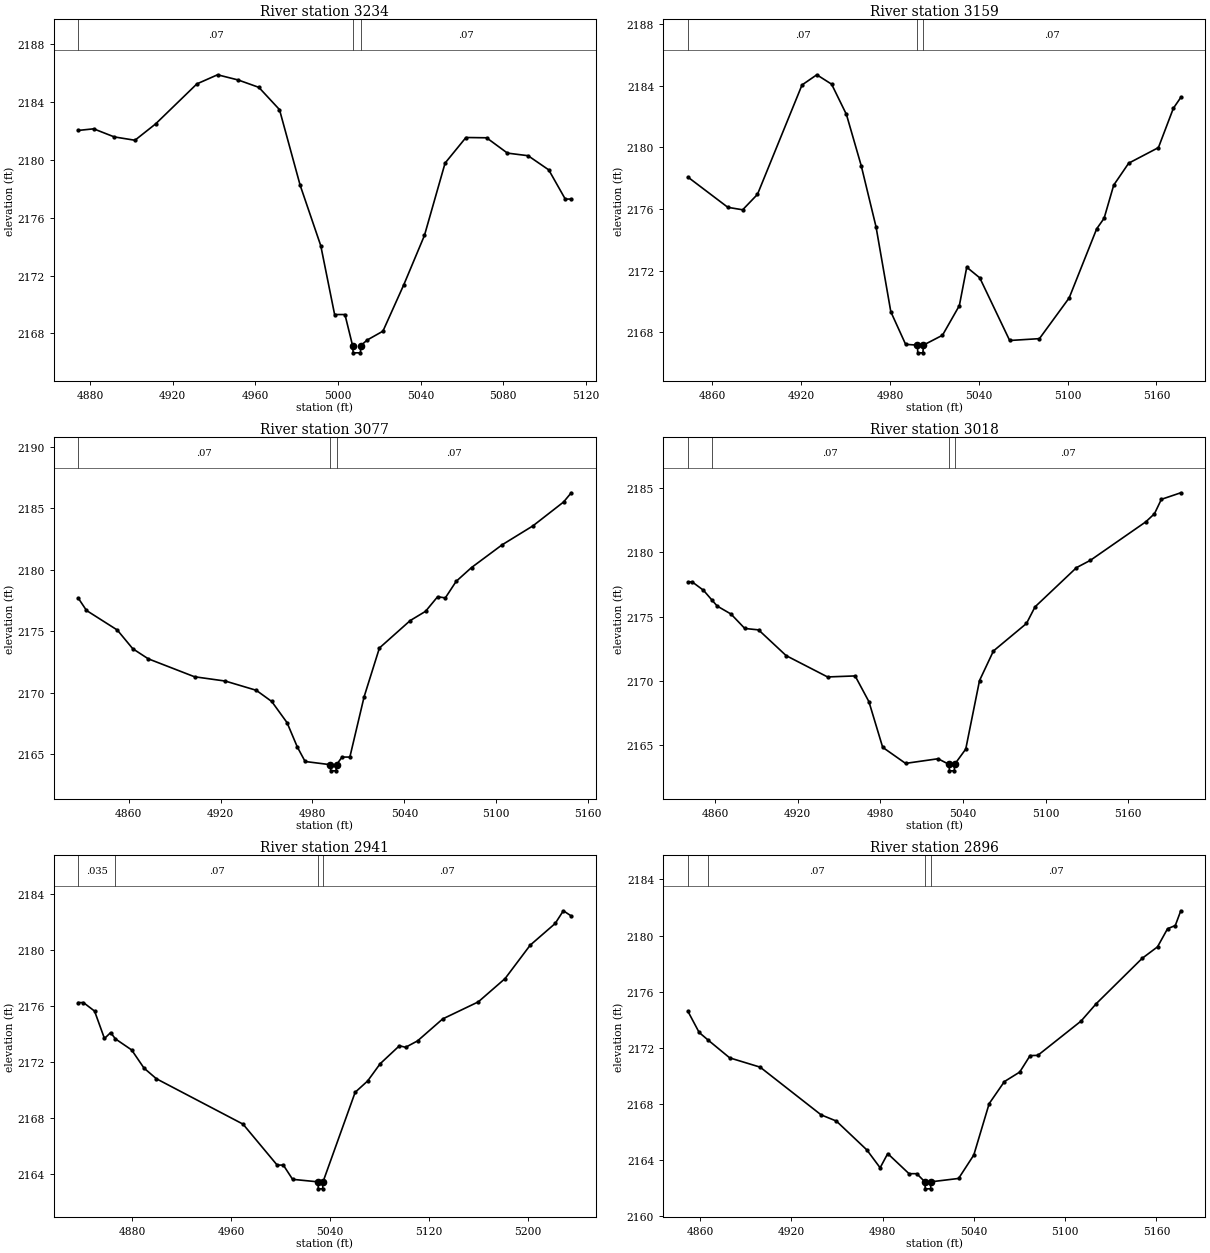
Type RM Length L Ch R = 1,3234,75,75,75
BEGIN DESCRIPTION:
Elm 82 4161
END DESCRIPTION:
XS GIS Cut Line= 3
      1534087.59      6763547.03      1534213.26      6763544.01
      1534325.81      6763534.01
#Sta/Elev= 30
  4874.3 2182.04  4881.7 2182.15  4891.7 2181.59  4901.7 2181.36  4911.7 2182.49
  4931.7 2185.26  4941.7 2185.89  4951.7 2185.53  4961.7 2185.02  4971.7 2183.48
  4981.7 2178.25  4991.7 2174.06  4998.4 2169.30  5003.4 2169.30  5007.1 2167.15
  5007.4 2166.65  5010.9 2166.65  5011.1 2167.15  5014.1 2167.53  5021.8 2168.15
  5031.9 2171.36  5041.9 2174.77  5051.9 2179.78  5062.0 2181.55  5072.0 2181.53
  5082.1 2180.47  5092.1 2180.29  5102.1 2179.31  5110.1 2177.29  5113.0 2177.29
#Mann=3,-1,0
  4874.3    0.07       0  5007.1    0.07       0  5011.1    0.07       0
Bank Sta=5007.1,5011.1
Exp/Cntr=0.3,0.1

Type RM Length L Ch R = 1,3159,82,82,82
BEGIN DESCRIPTION:
Elm 82 4160
END DESCRIPTION:
XS GIS Cut Line= 3
      1534097.97      6763609.53      1534269.85      6763604.32
      1534430.00      6763587.40
#Sta/Elev= 30
  4843.4 2178.07  4870.4 2176.11  4880.4 2175.95  4890.4 2176.95  4920.5 2184.04
  4930.5 2184.70  4940.5 2184.09  4950.5 2182.13  4960.5 2178.81  4970.5 2174.85
  4980.5 2169.34  4990.5 2167.23  4998.5 2167.18  4998.7 2166.68  5002.2 2166.68
  5002.5 2167.18  5015.4 2167.82  5026.8 2169.74  5031.8 2172.23  5040.6 2171.54
  5060.8 2167.48  5080.9 2167.60  5101.0 2170.24  5119.6 2174.72  5124.6 2175.40
  5131.1 2177.55  5141.2 2178.97  5161.3 2179.98  5171.4 2182.53  5176.4 2183.23
#Mann=3,-1,0
  4843.4    0.07       0  4998.5    0.07       0  5002.5    0.07       0
Bank Sta=4998.5,5002.5
Exp/Cntr=0.3,0.1

Type RM Length L Ch R = 1,3077,59,59,59
BEGIN DESCRIPTION:
Elm 82 4159
END DESCRIPTION:
XS GIS Cut Line= 3
      1534079.76      6763665.52      1534251.30      6763686.40
      1534399.99      6763678.55
#Sta/Elev= 30
  4827.2 2177.66  4832.5 2176.67  4852.6 2175.08  4862.7 2173.56  4872.8 2172.74
  4903.0 2171.28  4923.1 2170.93  4943.3 2170.18  4953.4 2169.27  4963.4 2167.55
  4970.1 2165.57  4975.2 2164.39  4991.7 2164.13  4991.9 2163.63  4995.4 2163.63
  4995.7 2164.13  4999.3 2164.75  5004.4 2164.75  5013.7 2169.65  5023.7 2173.62
  5043.8 2175.85  5053.8 2176.60  5061.7 2177.79  5066.7 2177.69  5073.8 2179.04
  5083.8 2180.16  5103.8 2182.01  5123.9 2183.55  5143.9 2185.49  5148.9 2186.24
#Mann=3,-1,0
  4827.2    0.07       0  4991.7    0.07       0  4995.7    0.07       0
Bank Sta=4991.7,4995.7
Exp/Cntr=0.3,0.1

Type RM Length L Ch R = 1,3018,77,77,77
BEGIN DESCRIPTION:
Elm 82 4158
END DESCRIPTION:
XS GIS Cut Line= 3
      1534053.74      6763724.12      1534213.15      6763731.94
      1534410.25      6763711.12
#Sta/Elev= 30
  4840.4 2177.69  4843.5 2177.69  4851.7 2177.04  4857.6 2176.31  4861.7 2175.81
  4871.7 2175.19  4881.7 2174.07  4891.7 2173.96  4911.7 2171.96  4941.8 2170.30
  4961.8 2170.38  4971.8 2168.38  4981.8 2164.83  4998.4 2163.58  5022.0 2163.94
  5030.0 2163.50  5030.3 2163.00  5033.8 2163.00  5034.0 2163.50  5042.1 2164.69
  5052.1 2170.02  5062.2 2172.32  5086.2 2174.46  5092.4 2175.75  5122.5 2178.80
  5132.6 2179.37  5172.8 2182.36  5179.1 2182.99  5184.1 2184.11  5198.2 2184.62
#Mann=4,-1,0
  4840.4   0.035       0  4857.6    0.07       0  5030.0    0.07       0
  5034.0    0.07       0
Bank Sta=5030,5034
Exp/Cntr=0.3,0.1

Type RM Length L Ch R = 1,2941,45,45,45
BEGIN DESCRIPTION:
Elm 82 4156
END DESCRIPTION:
XS GIS Cut Line= 3
      1534041.94      6763813.96      1534205.21      6763807.45
      1534437.87      6763772.29
#Sta/Elev= 30
  4836.6 2176.24  4840.7 2176.24  4849.7 2175.63  4857.7 2173.67  4862.7 2174.09
  4866.6 2173.64  4879.7 2172.85  4889.7 2171.55  4899.7 2170.79  4969.8 2167.54
  4997.4 2164.61  5002.4 2164.61  5009.9 2163.59  5030.5 2163.41  5030.7 2162.91
  5034.2 2162.91  5034.5 2163.41  5060.5 2169.82  5070.6 2170.63  5080.7 2171.86
  5096.3 2173.15  5101.3 2173.04  5111.0 2173.50  5131.3 2175.07  5160.1 2176.29
  5181.8 2177.96  5202.1 2180.35  5222.3 2181.90  5228.9 2182.81  5235.3 2182.44
#Mann=4,-1,0
  4836.6   0.035       0  4866.6    0.07       0  5030.5    0.07       0
  5034.5    0.07       0
Bank Sta=5030.5,5034.5
Exp/Cntr=0.3,0.1

Type RM Length L Ch R = 1,2896,49,49,49
BEGIN DESCRIPTION:
Elm 82 4157
END DESCRIPTION:
XS GIS Cut Line= 3
      1534057.59      6763862.14      1534205.33      6763851.73
      1534380.24      6763832.22
#Sta/Elev= 30
  4851.9 2174.61  4859.3 2173.10  4865.4 2172.54  4879.4 2171.29  4899.4 2170.63
  4939.5 2167.23  4949.5 2166.79  4969.6 2164.73  4978.3 2163.46  4983.3 2164.47
  4997.3 2163.04  5002.4 2163.04  5007.7 2162.46  5008.0 2161.96  5011.5 2161.96
  5011.7 2162.46  5029.9 2162.70  5039.9 2164.37  5050.0 2168.03  5060.0 2169.60
  5070.1 2170.28  5076.9 2171.45  5082.0 2171.47  5110.4 2173.91  5120.4 2175.15
  5150.6 2178.38  5160.7 2179.20  5167.3 2180.49  5172.4 2180.72  5176.0 2181.77
#Mann=4,-1,0
  4851.9   0.035       0  4865.4    0.07       0  5007.7    0.07       0
  5011.7    0.07       0
Bank Sta=5007.7,5011.7
Exp/Cntr=0.3,0.1

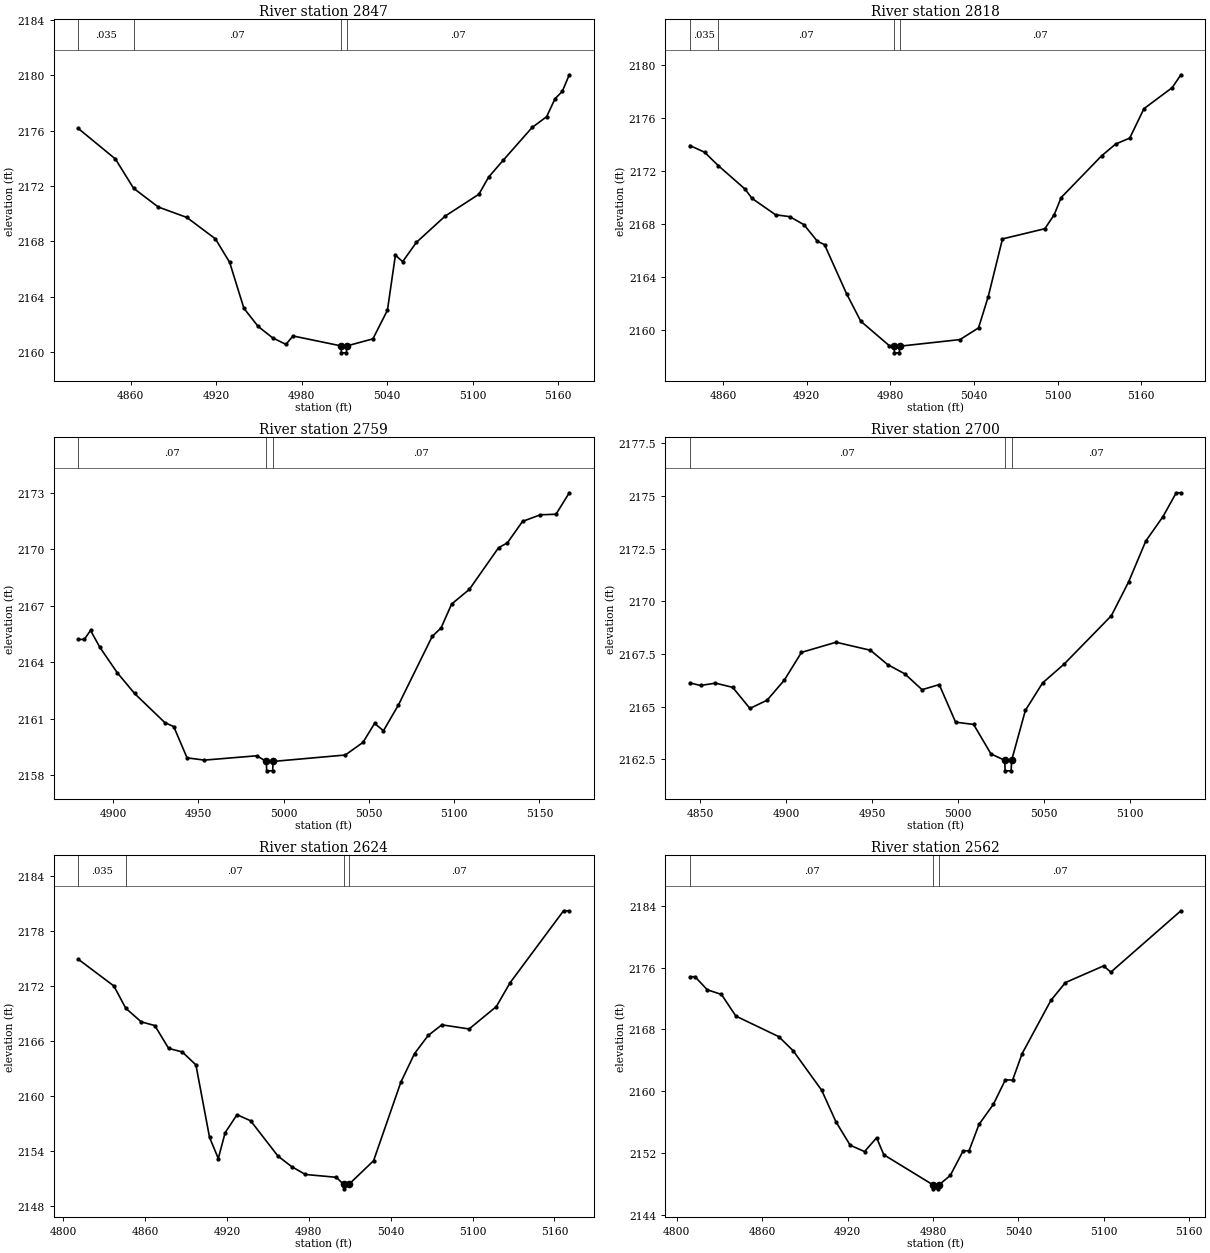
Type RM Length L Ch R = 1,2847,29,29,29
BEGIN DESCRIPTION:
Elm 82 2846.875
END DESCRIPTION:
XS GIS Cut Line= 3
      1534028.95      6763912.92      1534205.46      6763901.24
      1534370.68      6763871.38
#Sta/Elev= 30
  4823.1 2176.17  4849.2 2173.96  4861.9 2171.85  4879.3 2170.49  4899.3 2169.74
  4919.4 2168.19  4929.4 2166.49  4939.4 2163.17  4949.4 2161.86  4959.5 2161.04
  4968.9 2160.56  4973.9 2161.17  5007.7 2160.45  5007.9 2159.95  5011.4 2159.95
  5011.7 2160.45  5030.0 2160.96  5040.2 2163.03  5045.8 2167.01  5050.9 2166.54
  5060.5 2167.93  5080.8 2169.84  5104.4 2171.41  5111.3 2172.66  5121.5 2173.87
  5141.8 2176.24  5152.0 2177.02  5157.9 2178.32  5163.0 2178.85  5167.9 2180.05
#Mann=4,-1,0
  4823.1   0.035       0  4861.9    0.07       0  5007.7    0.07       0
  5011.7    0.07       0
Bank Sta=5007.7,5011.7
Exp/Cntr=0.3,0.1

Type RM Length L Ch R = 1,2818,59,59,59
BEGIN DESCRIPTION:
Elm 82 2817.92
END DESCRIPTION:
XS GIS Cut Line= 3
      1534044.58      6763961.10      1534207.35      6763929.85
      1534391.08      6763897.50
#Sta/Elev= 30
  4836.1 2173.93  4846.7 2173.42  4856.4 2172.42  4875.6 2170.65  4880.7 2169.94
  4897.6 2168.70  4907.8 2168.56  4918.0 2167.95  4927.6 2166.70  4932.7 2166.45
  4948.5 2162.75  4958.7 2160.67  4979.1 2158.83  4982.6 2158.78  4982.9 2158.28
  4986.4 2158.28  4986.6 2158.78  5029.9 2159.28  5043.2 2160.16  5050.2 2162.53
  5060.4 2166.88  5090.8 2167.65  5097.5 2168.70  5102.5 2170.00  5131.5 2173.15
  5141.6 2174.04  5151.7 2174.49  5161.9 2176.71  5182.2 2178.30  5188.4 2179.27
#Mann=4,-1,0
  4836.1   0.035       0  4856.4    0.07       0  4982.6    0.07       0
  4986.6    0.07       0
Bank Sta=4982.6,4986.6
Exp/Cntr=0.3,0.1

Type RM Length L Ch R = 1,2759,59,59,59
BEGIN DESCRIPTION:
Elm 82 2759.27
END DESCRIPTION:
XS GIS Cut Line= 3
      1534092.73      6764014.49      1534204.75      6763989.74
      1534371.31      6763941.97
#Sta/Elev= 30
  4879.5 2165.22  4883.0 2165.22  4886.7 2165.70  4892.1 2164.81  4902.3 2163.46
  4912.5 2162.35  4930.3 2160.80  4935.5 2160.59  4943.3 2158.93  4953.5 2158.81
  4984.2 2159.04  4989.8 2158.74  4990.0 2158.24  4993.5 2158.24  4993.8 2158.74
  5036.1 2159.08  5046.5 2159.75  5053.3 2160.76  5058.5 2160.37  5067.3 2161.74
  5087.1 2165.38  5092.3 2165.83  5098.5 2167.10  5108.9 2167.88  5126.0 2170.09
  5131.2 2170.35  5140.1 2171.49  5150.5 2171.84  5159.7 2171.87  5167.5 2173.01
#Mann=3,-1,0
  4879.5    0.07       0  4989.8    0.07       0  4993.8    0.07       0
Bank Sta=4989.8,4993.8
Exp/Cntr=0.3,0.1

Type RM Length L Ch R = 1,2700,76,76,76
BEGIN DESCRIPTION:
Elm 82 2699.52
END DESCRIPTION:
XS GIS Cut Line= 3
      1534090.15      6764043.13      1534249.02      6764035.31
      1534375.35      6764030.10
#Sta/Elev= 30
  4844.0 2166.13  4850.2 2166.01  4858.9 2166.12  4868.9 2165.92  4878.9 2164.92
  4888.9 2165.31  4898.9 2166.26  4908.9 2167.58  4929.0 2168.06  4949.0 2167.68
  4959.0 2167.00  4969.0 2166.56  4979.0 2165.81  4989.0 2166.05  4998.5 2164.27
  5009.0 2164.16  5019.1 2162.76  5027.1 2162.46  5027.3 2161.96  5030.8 2161.96
  5031.1 2162.46  5039.1 2164.83  5049.1 2166.13  5061.7 2167.03  5089.1 2169.32
  5099.1 2170.92  5109.1 2172.86  5119.1 2174.02  5126.8 2175.15  5129.5 2175.15
#Mann=3,-1,0
  4844.0    0.07       0  5027.1    0.07       0  5031.1    0.07       0
Bank Sta=5027.1,5031.1
Exp/Cntr=0.3,0.1

Type RM Length L Ch R = 1,2624,62,62,62
BEGIN DESCRIPTION:
Elm 82 2624.37
END DESCRIPTION:
XS GIS Cut Line= 3
      1534028.98      6764109.53      1534215.16      6764097.81
      1534388.39      6764100.42
#Sta/Elev= 30
  4811.1 2174.89  4837.2 2171.97  4845.9 2169.54  4857.2 2168.06  4867.2 2167.65
  4877.3 2165.16  4887.3 2164.77  4897.3 2163.36  4907.3 2155.44  4913.7 2153.14
  4918.7 2155.95  4927.4 2157.92  4937.4 2157.26  4957.4 2153.41  4967.4 2152.26
  4977.5 2151.40  5000.1 2151.09  5005.5 2150.33  5005.7 2149.83  5009.5 2150.33
  5027.5 2152.90  5047.5 2161.48  5057.5 2164.59  5067.5 2166.57  5077.5 2167.73
  5097.5 2167.28  5117.5 2169.73  5127.5 2172.32  5166.7 2180.18  5170.9 2180.18
#Mann=4,-1,0
  4811.1   0.035       0  4845.9    0.07       0  5005.5    0.07       0
  5009.5    0.07       0
Bank Sta=5005.5,5009.5
Exp/Cntr=0.3,0.1

Type RM Length L Ch R = 1,2562,33,33,33
BEGIN DESCRIPTION:
Elm 82 2562.3
END DESCRIPTION:
XS GIS Cut Line= 3
      1534062.85      6764165.52      1534258.13      6764147.29
      1534405.24      6764125.16
#Sta/Elev= 30
  4809.2 2174.83  4812.8 2174.83  4821.4 2173.14  4831.4 2172.53  4841.5 2169.73
  4871.6 2167.07  4881.7 2165.25  4901.8 2160.12  4911.8 2156.04  4921.8 2153.00
  4931.9 2152.18  4940.4 2153.97  4945.4 2151.77  4980.1 2147.85  4980.3 2147.35
  4983.8 2147.35  4984.1 2147.85  4992.1 2149.08  5001.2 2152.28  5005.3 2152.28
  5012.3 2155.70  5022.4 2158.30  5030.8 2161.47  5035.9 2161.44  5042.6 2164.87
  5062.8 2171.76  5073.0 2174.07  5099.8 2176.23  5104.9 2175.42  5154.1 2183.37
#Mann=3,-1,0
  4809.2    0.07       0  4980.1    0.07       0  4984.1    0.07       0
Bank Sta=4980.1,4984.1
Exp/Cntr=0.3,0.1

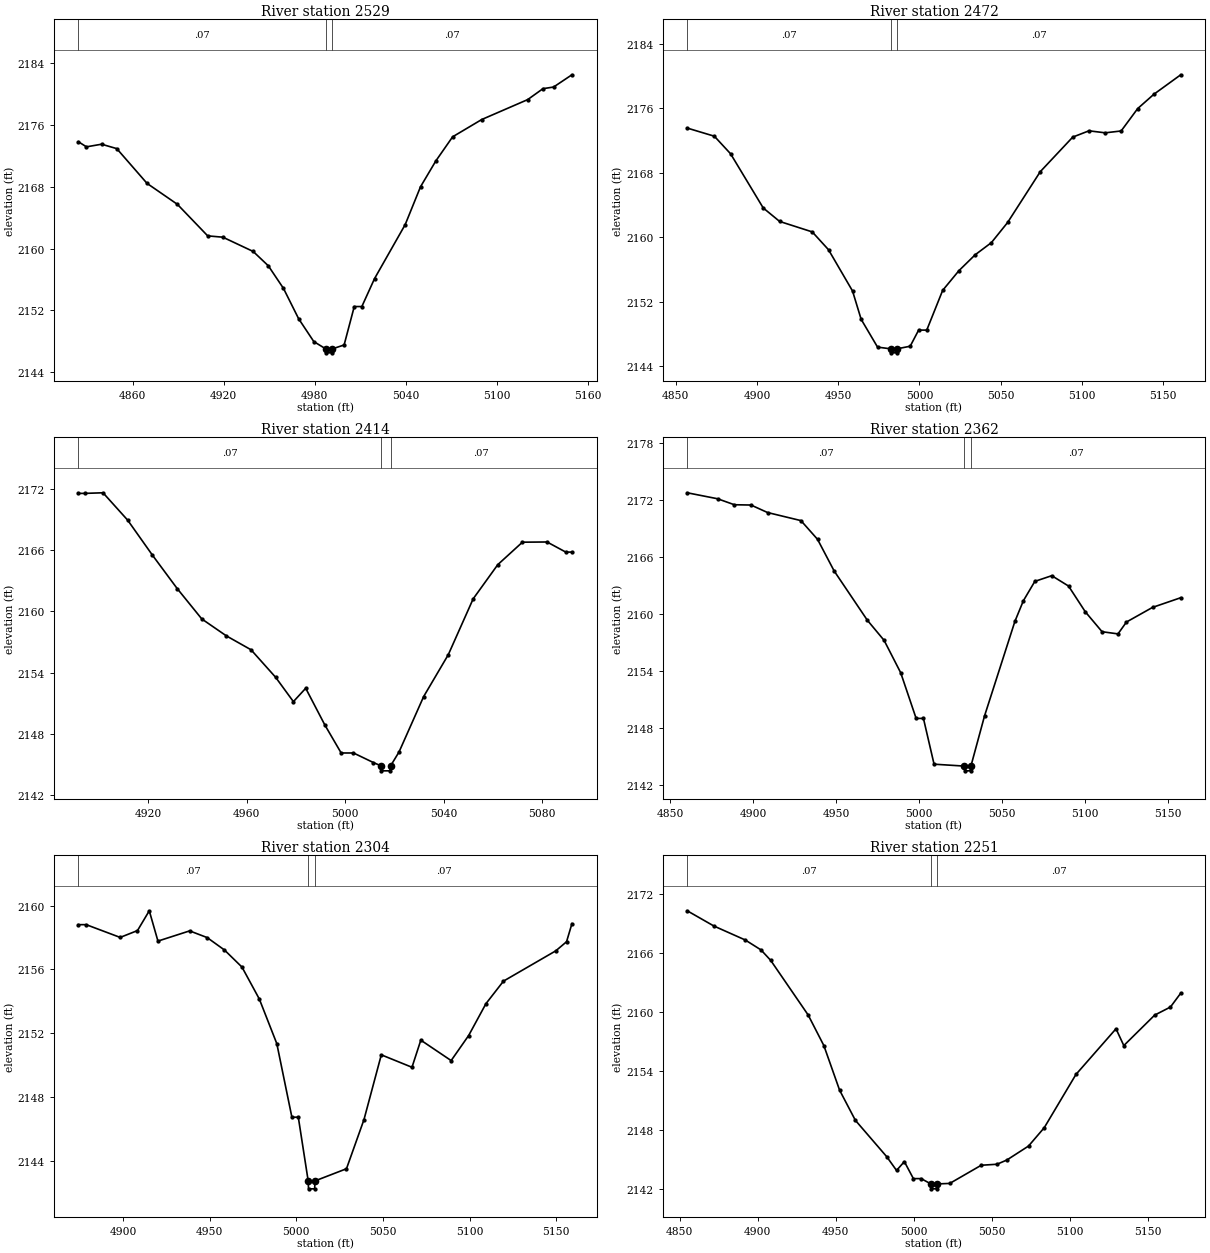
Type RM Length L Ch R = 1,2529,57,57,57
BEGIN DESCRIPTION:
Elm 82 2528.7
END DESCRIPTION:
XS GIS Cut Line= 3
      1534079.70      6764181.15      1534263.34      6764181.15
      1534403.95      6764161.62
#Sta/Elev= 30
  4824.1 2173.84  4829.4 2173.18  4839.4 2173.52  4849.4 2172.95  4869.4 2168.44
  4889.4 2165.73  4909.4 2161.64  4919.4 2161.47  4939.4 2159.62  4949.4 2157.76
  4959.4 2154.83  4969.4 2150.90  4979.4 2147.94  4987.4 2146.98  4987.6 2146.48
  4991.1 2146.48  4991.4 2146.98  4999.4 2147.50  5006.1 2152.48  5011.1 2152.48
  5019.5 2156.11  5039.7 2163.10  5049.8 2168.00  5059.9 2171.35  5071.0 2174.48
  5090.2 2176.72  5120.5 2179.30  5130.6 2180.72  5137.6 2180.93  5149.7 2182.52
#Mann=3,-1,0
  4824.1    0.07       0  4987.4    0.07       0  4991.4    0.07       0
Bank Sta=4987.4,4991.4
Exp/Cntr=0.3,0.1

Type RM Length L Ch R = 1,2472,58,58,58
BEGIN DESCRIPTION:
Elm 82 2472.11
END DESCRIPTION:
XS GIS Cut Line= 3
      1534108.41      6764222.82      1534250.32      6764237.14
      1534411.50      6764231.98
#Sta/Elev= 30
  4857.0 2173.53  4873.7 2172.52  4883.7 2170.34  4903.8 2163.62  4913.9 2161.95
  4934.0 2160.65  4944.0 2158.44  4958.8 2153.32  4964.1 2149.81  4974.2 2146.36
  4982.2 2146.15  4982.5 2145.65  4986.0 2145.65  4986.2 2146.15  4994.3 2146.47
  4999.5 2148.47  5004.5 2148.47  5014.3 2153.40  5024.3 2155.84  5034.3 2157.81
  5044.3 2159.32  5054.3 2161.82  5074.4 2168.12  5094.4 2172.41  5104.4 2173.19
  5114.4 2172.94  5124.2 2173.17  5134.4 2175.95  5144.4 2177.73  5160.9 2180.14
#Mann=3,-1,0
  4857.0    0.07       0  4982.2    0.07       0  4986.2    0.07       0
Bank Sta=4982.2,4986.2
Exp/Cntr=0.3,0.1

Type RM Length L Ch R = 1,2414,52,52,52
BEGIN DESCRIPTION:
Elm 82 2413.643
END DESCRIPTION:
XS GIS Cut Line= 3
      1534105.01      6764288.00      1534213.14      6764281.94
      1534305.04      6764288.00
#Sta/Elev= 29
  4891.7 2171.55  4894.2 2171.55  4901.7 2171.61  4911.7 2168.93  4921.7 2165.52
  4931.8 2162.23  4941.8 2159.25  4951.8 2157.59  4961.8 2156.23  4971.8 2153.53
  4979.0 2151.15  4984.0 2152.46  4991.8 2148.85  4998.4 2146.12  5003.4 2146.12
  5011.5 2145.18  5014.5 2144.87  5014.7 2144.37  5018.2 2144.37  5018.5 2144.87
  5021.9 2146.22  5031.9 2151.65  5041.9 2155.75  5052.0 2161.22  5062.0 2164.57
  5072.0 2166.77  5082.0 2166.79  5089.6 2165.80  5092.1 2165.80
#Mann=3,-1,0
  4891.7    0.07       0  5014.5    0.07       0  5018.5    0.07       0
Bank Sta=5014.5,5018.5
Exp/Cntr=0.3,0.1

Type RM Length L Ch R = 1,2362,58,58,58
BEGIN DESCRIPTION:
Elm 82 2362.16
END DESCRIPTION:
XS GIS Cut Line= 3
      1534066.69      6764323.07      1534208.65      6764332.19
      1534361.76      6764307.74
#Sta/Elev= 30
  4860.2 2172.79  4878.5 2172.16  4888.6 2171.53  4898.6 2171.50  4908.6 2170.71
  4928.7 2169.86  4938.7 2167.89  4948.7 2164.56  4968.7 2159.37  4978.8 2157.25
  4988.8 2153.84  4998.1 2149.03  5002.5 2149.03  5008.9 2144.21  5027.1 2144.01
  5027.4 2143.51  5030.9 2143.51  5031.1 2144.01  5039.3 2149.29  5057.6 2159.25
  5062.7 2161.42  5069.6 2163.46  5079.8 2164.06  5089.9 2162.97  5100.0 2160.26
  5110.1 2158.16  5119.7 2157.93  5124.8 2159.18  5140.5 2160.72  5157.5 2161.74
#Mann=3,-1,0
  4860.2    0.07       0  5027.1    0.07       0  5031.1    0.07       0
Bank Sta=5027.1,5031.1
Exp/Cntr=0.3,0.1

Type RM Length L Ch R = 1,2304,53,53,53
BEGIN DESCRIPTION:
Elm 82 2303.52
END DESCRIPTION:
XS GIS Cut Line= 3
      1534081.03      6764379.06      1534207.35      6764390.78
      1534364.26      6764372.78
#Sta/Elev= 30
  4874.3 2158.81  4878.8 2158.81  4898.4 2158.01  4908.4 2158.44  4915.2 2159.68
  4920.2 2157.78  4938.5 2158.42  4948.6 2158.00  4958.6 2157.22  4968.7 2156.15
  4978.7 2154.15  4988.8 2151.35  4997.5 2146.74  5001.2 2146.74  5006.9 2142.75
  5007.1 2142.25  5010.6 2142.25  5010.9 2142.75  5029.0 2143.51  5039.1 2146.59
  5049.1 2150.65  5066.8 2149.87  5071.9 2151.57  5089.4 2150.29  5099.5 2151.86
  5109.5 2153.86  5119.6 2155.27  5149.8 2157.17  5156.0 2157.74  5159.1 2158.87
#Mann=3,-1,0
  4874.3    0.07       0  5006.9    0.07       0  5010.9    0.07       0
Bank Sta=5006.9,5010.9
Exp/Cntr=0.3,0.1

Type RM Length L Ch R = 1,2251,54,54,54
BEGIN DESCRIPTION:
Elm 82 2251.23
END DESCRIPTION:
XS GIS Cut Line= 3
      1534068.05      6764459.79      1534213.86      6764441.56
      1534381.54      6764417.06
#Sta/Elev= 30
  4854.8 2170.30  4871.9 2168.75  4892.0 2167.33  4902.1 2166.32  4908.3 2165.26
  4932.3 2159.71  4942.4 2156.59  4952.5 2152.05  4962.6 2148.99  4982.7 2145.29
  4989.0 2143.89  4994.0 2144.79  4999.8 2143.06  5004.8 2143.06  5011.0 2142.52
  5011.2 2142.02  5014.7 2142.02  5015.0 2142.52  5023.1 2142.57  5043.3 2144.42
  5053.4 2144.52  5059.7 2144.95  5073.6 2146.37  5083.7 2148.24  5104.0 2153.65
  5129.7 2158.30  5134.7 2156.59  5154.5 2159.69  5164.6 2160.51  5171.2 2161.92
#Mann=3,-1,0
  4854.8    0.07       0  5011.0    0.07       0  5015.0    0.07       0
Bank Sta=5011,5015
Exp/Cntr=0.3,0.1

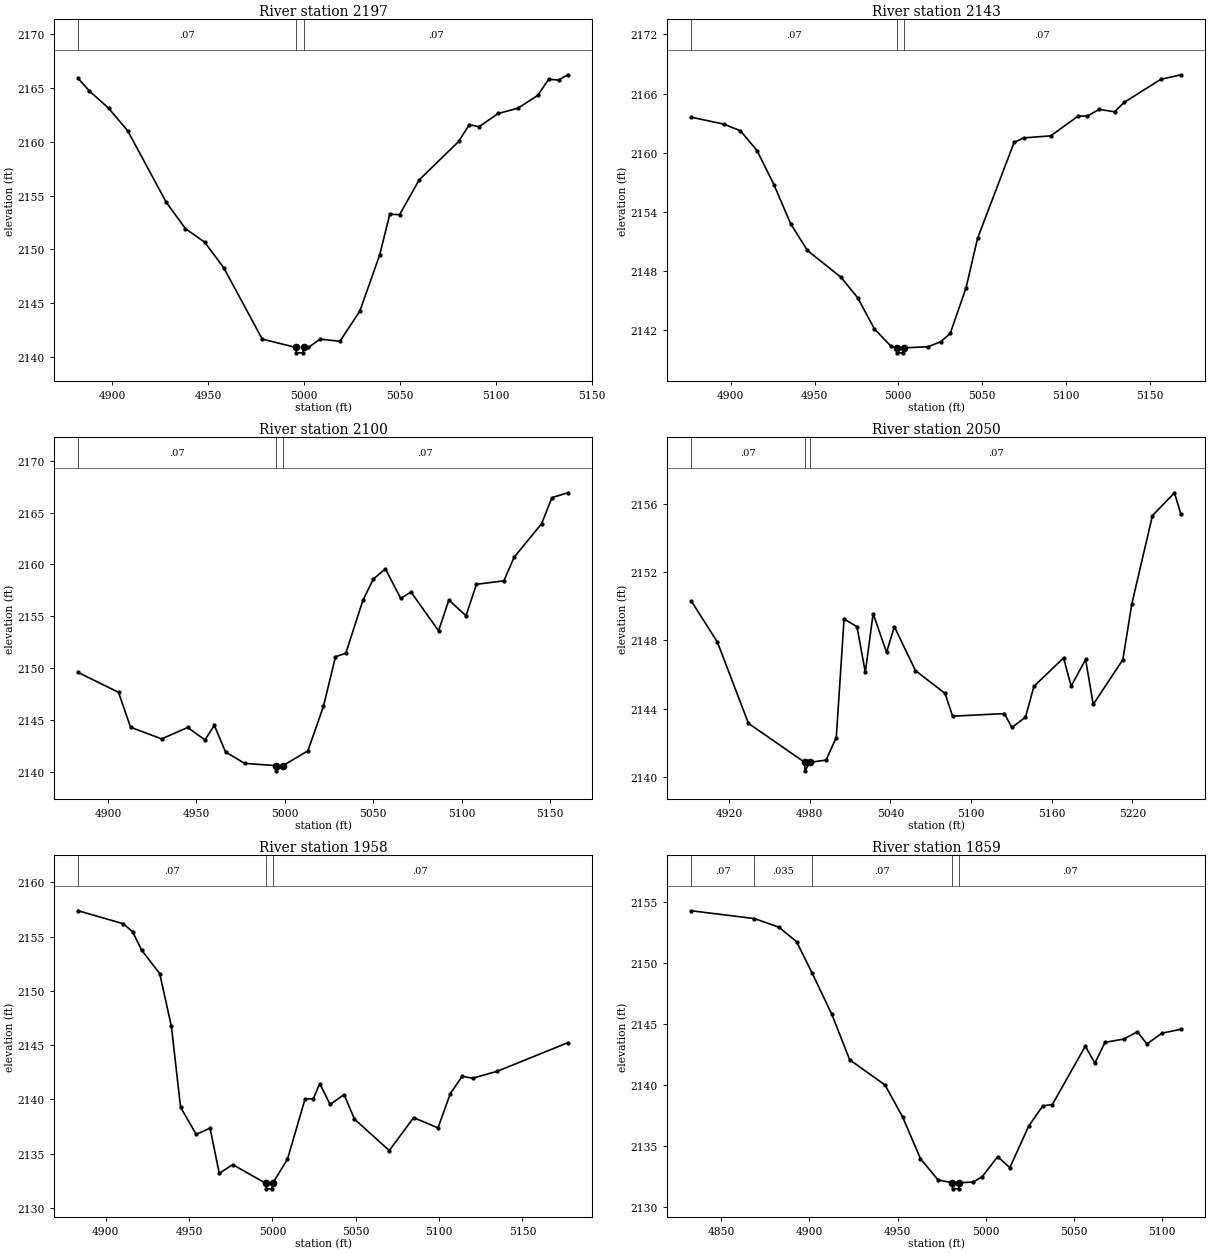
Type RM Length L Ch R = 1,2197,54,54,54
BEGIN DESCRIPTION:
Elm 82 2197.02
END DESCRIPTION:
XS GIS Cut Line= 3
      1534129.21      6764489.74      1534249.02      6764483.23
      1534380.27      6764450.74
#Sta/Elev= 30
  4882.3 2165.90  4888.1 2164.74  4898.1 2163.14  4908.1 2161.03  4928.2 2154.38
  4938.2 2151.93  4948.2 2150.67  4958.2 2148.28  4978.2 2141.66  4995.8 2140.88
  4996.0 2140.38  4999.5 2140.38  4999.8 2140.88  5002.3 2140.88  5008.4 2141.66
  5018.7 2141.45  5029.1 2144.27  5039.4 2149.47  5044.7 2153.27  5049.8 2153.23
  5060.0 2156.46  5080.6 2160.04  5086.1 2161.60  5091.2 2161.41  5101.2 2162.64
  5111.5 2163.13  5121.8 2164.32  5127.5 2165.82  5132.7 2165.75  5137.5 2166.24
#Mann=3,-1,0
  4882.3    0.07       0  4995.8    0.07       0  4999.8    0.07       0
Bank Sta=4995.8,4999.8
Exp/Cntr=0.3,0.1

Type RM Length L Ch R = 1,2143,43,43,43
BEGIN DESCRIPTION:
Elm 82 2142.99
END DESCRIPTION:
XS GIS Cut Line= 3
      1534135.74      6764539.22      1534260.74      6764535.31
      1534407.91      6764455.87
#Sta/Elev= 30
  4876.4 2163.61  4895.7 2162.91  4905.7 2162.24  4915.7 2160.21  4925.7 2156.78
  4935.7 2152.81  4945.7 2150.10  4965.7 2147.39  4975.7 2145.31  4985.7 2142.15
  4995.7 2140.37  4999.1 2140.22  4999.3 2139.72  5002.8 2139.72  5003.1 2140.22
  5017.7 2140.34  5025.4 2140.85  5031.0 2141.70  5040.4 2146.30  5047.3 2151.33
  5069.1 2161.05  5074.8 2161.51  5091.0 2161.72  5107.2 2163.71  5112.9 2163.74
  5119.9 2164.40  5129.1 2164.16  5134.8 2165.11  5156.7 2167.45  5168.7 2167.91
#Mann=3,-1,0
  4876.4    0.07       0  4999.1    0.07       0  5003.1    0.07       0
Bank Sta=4999.1,5003.1
Exp/Cntr=0.3,0.1

Type RM Length L Ch R = 1,2100,50,50,50
BEGIN DESCRIPTION:
Elm 82 2100.21
END DESCRIPTION:
XS GIS Cut Line= 3
      1534177.43      6764610.82      1534286.78      6764567.87
      1534423.48      6764485.85
#Sta/Elev= 30
  4883.2 2149.59  4906.0 2147.68  4912.8 2144.31  4930.4 2143.19  4945.1 2144.29
  4954.9 2143.09  4960.2 2144.49  4966.5 2141.93  4977.3 2140.83  4995.0 2140.61
  4995.3 2140.11  4999.0 2140.61  5013.1 2142.04  5021.9 2146.33  5028.7 2151.11
  5034.5 2151.44  5044.2 2156.54  5050.1 2158.59  5056.9 2159.58  5065.6 2156.73
  5071.4 2157.34  5087.0 2153.61  5092.8 2156.57  5102.5 2155.06  5108.4 2158.09
  5123.9 2158.42  5129.7 2160.69  5145.3 2163.94  5151.1 2166.44  5160.1 2166.91
#Mann=3,-1,0
  4883.2    0.07       0  4995.0    0.07       0  4999.0    0.07       0
Bank Sta=4995,4999
Exp/Cntr=0.3,0.1

Type RM Length L Ch R = 1,2050,92,92,92
BEGIN DESCRIPTION:
Elm 82 2049.72
END DESCRIPTION:
XS GIS Cut Line= 3
      1534228.18      6764657.71      1534375.32      6764573.07
      1534547.31      6764663.59
#Sta/Elev= 30
  4892.0 2150.30  4911.4 2147.90  4934.5 2143.14  4976.3 2140.86  4976.5 2140.36
  4980.3 2140.86  4992.2 2140.99  4999.8 2142.31  5005.6 2149.25  5015.2 2148.80
  5021.4 2146.13  5027.2 2149.56  5037.2 2147.30  5043.0 2148.80  5058.7 2146.23
  5080.7 2144.89  5086.3 2143.56  5124.8 2143.71  5130.4 2142.90  5140.5 2143.50
  5146.8 2145.31  5168.8 2146.97  5174.5 2145.32  5185.2 2146.88  5190.9 2144.25
  5212.9 2146.87  5219.6 2150.14  5234.9 2155.30  5251.3 2156.64  5256.1 2155.37
#Mann=3,-1,0
  4892.0    0.07       0  4976.3    0.07       0  4980.3    0.07       0
Bank Sta=4976.3,4980.3
Exp/Cntr=0.3,0.1

Type RM Length L Ch R = 1,1958,99,99,99
BEGIN DESCRIPTION:
Elm 82 1957.75
END DESCRIPTION:
XS GIS Cut Line= 3
      1534280.29      6764716.30      1534409.17      6764659.01
      1534531.45      6764750.40
#Sta/Elev= 30
  4883.5 2157.37  4910.5 2156.18  4916.1 2155.44  4921.6 2153.74  4932.4 2151.58
  4939.4 2146.72  4944.9 2139.27  4954.3 2136.78  4962.6 2137.35  4968.1 2133.19
  4976.2 2133.99  4996.1 2132.26  4996.3 2131.76  4999.8 2131.76  5000.1 2132.26
  5009.0 2134.48  5019.6 2140.05  5024.5 2140.05  5028.4 2141.45  5034.6 2139.53
  5043.0 2140.44  5049.2 2138.18  5070.1 2135.29  5084.7 2138.32  5099.3 2137.37
  5106.7 2140.53  5113.8 2142.12  5120.1 2141.95  5134.7 2142.58  5177.2 2145.22
#Mann=3,-1,0
  4883.5    0.07       0  4996.1    0.07       0  5000.1    0.07       0
Bank Sta=4996.1,5000.1
Exp/Cntr=0.3,0.1

Type RM Length L Ch R = 1,1859,55,55,55
BEGIN DESCRIPTION:
Elm 82 1858.5
END DESCRIPTION:
XS GIS Cut Line= 3
      1534285.49      6764755.37      1534458.65      6764742.35
      1534554.98      6764781.40
#Sta/Elev= 30
  4833.0 2154.29  4868.8 2153.65  4882.7 2152.94  4892.7 2151.75  4901.5 2149.18
  4912.7 2145.78  4922.8 2142.06  4942.8 2140.00  4952.8 2137.37  4962.9 2133.95
  4972.9 2132.20  4980.9 2131.97  4981.2 2131.47  4984.7 2131.47  4984.9 2131.97
  4992.9 2132.03  4998.0 2132.48  5006.7 2134.11  5013.6 2133.21  5024.3 2136.62
  5032.3 2138.28  5037.7 2138.39  5056.4 2143.18  5061.8 2141.78  5067.5 2143.49
  5078.2 2143.76  5085.9 2144.36  5091.3 2143.36  5099.8 2144.24  5110.6 2144.57
#Mann=5,-1,0
  4833.0    0.07       0  4868.8   0.035       0  4901.5    0.07       0
  4980.9    0.07       0  4984.9    0.07       0
Bank Sta=4980.9,4984.9
Exp/Cntr=0.3,0.1

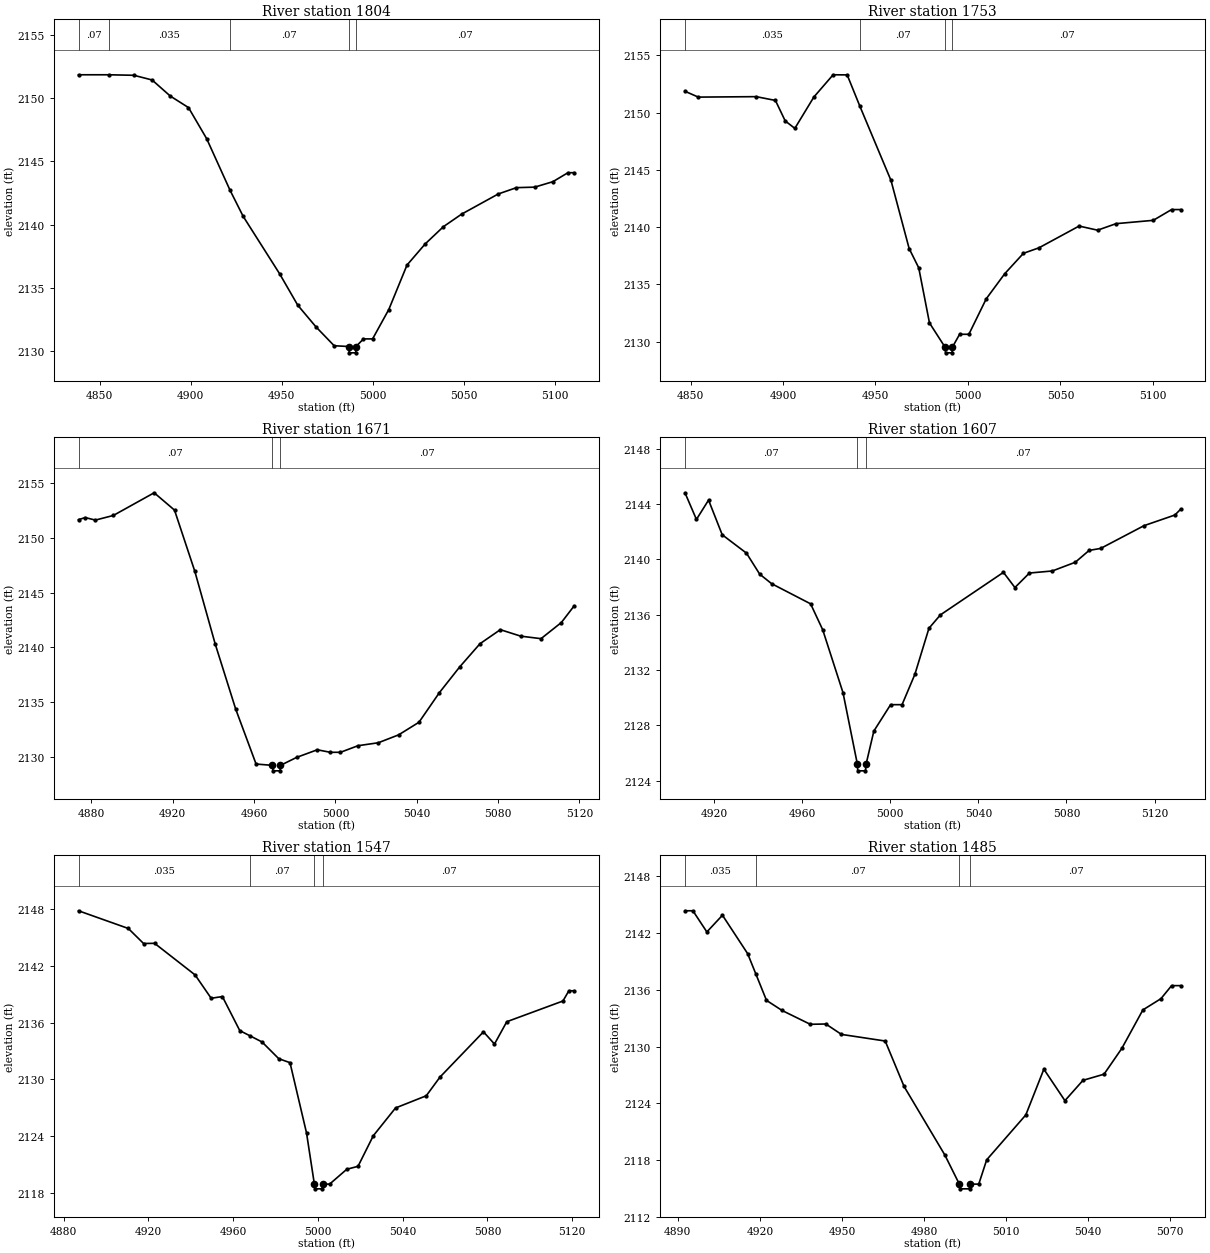
Type RM Length L Ch R = 1,1804,51,51,51
BEGIN DESCRIPTION:
Elm 82 1804.16
END DESCRIPTION:
XS GIS Cut Line= 3
      1534294.63      6764800.94      1534452.14      6764797.03
      1534566.71      6764793.13
#Sta/Elev= 30
  4838.4 2151.84  4855.0 2151.84  4868.8 2151.80  4878.8 2151.43  4888.8 2150.16
  4898.8 2149.25  4908.8 2146.79  4921.6 2142.73  4928.8 2140.67  4948.8 2136.14
  4958.8 2133.65  4968.8 2131.94  4978.8 2130.45  4986.8 2130.39  4987.1 2129.89
  4990.6 2129.89  4990.8 2130.39  4994.9 2130.99  4999.9 2130.99  5008.8 2133.31
  5018.8 2136.82  5028.8 2138.49  5038.8 2139.85  5048.8 2140.84  5068.9 2142.43
  5078.9 2142.93  5088.9 2142.97  5098.9 2143.40  5107.2 2144.11  5110.6 2144.11
#Mann=5,-1,0
  4838.4    0.07       0  4855.0   0.035       0  4921.6    0.07       0
  4986.8    0.07       0  4990.8    0.07       0
Bank Sta=4986.8,4990.8
Exp/Cntr=0.3,0.1

Type RM Length L Ch R = 1,1753,82,82,82
BEGIN DESCRIPTION:
Elm 82 1752.84
END DESCRIPTION:
XS GIS Cut Line= 3
      1534318.07      6764888.17      1534461.26      6764846.51
      1534579.78      6764837.39
#Sta/Elev= 30
  4847.0 2151.86  4854.2 2151.35  4885.5 2151.39  4895.9 2151.06  4901.2 2149.27
  4906.4 2148.62  4916.7 2151.36  4927.1 2153.30  4934.7 2153.29  4941.6 2150.54
  4958.4 2144.07  4968.2 2138.13  4973.4 2136.44  4979.2 2131.63  4987.6 2129.52
  4987.9 2129.02  4991.4 2129.02  4991.6 2129.52  4995.5 2130.64  5000.5 2130.64
  5009.9 2133.74  5019.9 2135.93  5030.0 2137.71  5038.4 2138.19  5060.1 2140.09
  5070.1 2139.73  5080.1 2140.30  5100.2 2140.59  5110.1 2141.53  5115.0 2141.53
#Mann=4,-1,0
  4847.0   0.035       0  4941.6    0.07       0  4987.6    0.07       0
  4991.6    0.07       0
Bank Sta=4987.6,4991.6
Exp/Cntr=0.3,0.1

Type RM Length L Ch R = 1,1671,64,64,64
BEGIN DESCRIPTION:
Elm 82 1671.35
END DESCRIPTION:
XS GIS Cut Line= 3
      1534377.95      6764923.33      1534502.92      6764914.22
      1534621.31      6764914.22
#Sta/Elev= 30
  4873.7 2151.65  4877.0 2151.84  4882.0 2151.61  4890.8 2152.03  4910.9 2154.10
  4920.9 2152.52  4930.9 2146.93  4940.9 2140.32  4951.0 2134.37  4961.0 2129.37
  4969.0 2129.25  4969.3 2128.75  4972.8 2128.75  4973.0 2129.25  4981.0 2129.98
  4991.1 2130.67  4997.5 2130.44  5002.5 2130.44  5011.1 2131.04  5021.1 2131.31
  5031.1 2132.03  5041.1 2133.18  5051.1 2135.87  5061.1 2138.22  5071.1 2140.34
  5081.1 2141.62  5091.1 2141.03  5101.1 2140.80  5111.1 2142.27  5117.4 2143.79
#Mann=3,-1,0
  4873.7    0.07       0  4969.0    0.07       0  4973.0    0.07       0
Bank Sta=4969,4973
Exp/Cntr=0.3,0.1

Type RM Length L Ch R = 1,1607,60,60,60
BEGIN DESCRIPTION:
Elm 82 1606.63
END DESCRIPTION:
XS GIS Cut Line= 3
      1534419.58      6765017.09      1534509.43      6764976.72
      1534630.92      6764941.83
#Sta/Elev= 30
  4906.9 2144.83  4912.1 2142.90  4917.6 2144.30  4923.8 2141.79  4934.8 2140.46
  4940.8 2138.94  4946.2 2138.25  4963.9 2136.79  4969.4 2134.91  4978.6 2130.36
  4985.1 2125.20  4985.3 2124.70  4988.8 2124.70  4989.1 2125.20  4992.6 2127.58
  5000.2 2129.49  5005.4 2129.49  5011.2 2131.68  5017.6 2135.02  5022.8 2135.99
  5051.4 2139.07  5056.6 2137.97  5063.2 2139.02  5073.6 2139.17  5084.0 2139.80
  5090.3 2140.66  5095.5 2140.80  5115.2 2142.45  5129.2 2143.22  5131.8 2143.64
#Mann=3,-1,0
  4906.9    0.07       0  4985.1    0.07       0  4989.1    0.07       0
Bank Sta=4985.1,4989.1
Exp/Cntr=0.3,0.1

Type RM Length L Ch R = 1,1547,62,62,62
BEGIN DESCRIPTION:
Elm 82 1546.63
END DESCRIPTION:
XS GIS Cut Line= 3
      1534402.66      6765073.08      1534510.74      6765037.92
      1534625.33      6765001.46
#Sta/Elev= 30
  4887.0 2147.82  4910.5 2145.95  4917.7 2144.36  4922.9 2144.38  4942.0 2141.04
  4949.6 2138.57  4954.9 2138.75  4963.1 2135.15  4968.1 2134.58  4973.6 2133.95
  4981.5 2132.18  4986.8 2131.76  4994.6 2124.33  4998.3 2118.92  4998.5 2118.42
  5002.0 2118.42  5002.3 2118.92  5005.5 2118.92  5013.6 2120.49  5018.9 2120.80
  5026.1 2124.03  5036.6 2126.97  5051.1 2128.26  5057.6 2130.24  5078.1 2135.02
  5083.3 2133.73  5089.1 2136.09  5115.6 2138.28  5118.4 2139.36  5120.9 2139.36
#Mann=4,-1,0
  4887.0   0.035       0  4968.1    0.07       0  4998.3    0.07       0
  5002.3    0.07       0
Bank Sta=4998.3,5002.3
Exp/Cntr=0.3,0.1

Type RM Length L Ch R = 1,1485,57,57,57
BEGIN DESCRIPTION:
Elm 82 1485.174
END DESCRIPTION:
XS GIS Cut Line= 3
      1534454.99      6765138.01      1534548.86      6765085.83
      1534605.04      6765037.97
#Sta/Elev= 30
  4892.6 2144.36  4895.5 2144.36  4900.6 2142.12  4906.3 2143.89  4915.5 2139.83
  4918.5 2137.68  4922.4 2134.88  4928.1 2133.81  4938.4 2132.35  4944.1 2132.38
  4949.8 2131.28  4965.8 2130.58  4972.7 2125.77  4987.6 2118.52  4992.9 2115.44
  4993.2 2114.94  4996.7 2114.94  4996.9 2115.44  5000.0 2115.44  5002.9 2118.01
  5017.2 2122.76  5023.8 2127.60  5031.5 2124.27  5038.1 2126.42  5045.8 2127.07
  5052.3 2129.80  5060.0 2133.87  5066.6 2135.06  5070.5 2136.44  5073.8 2136.44
#Mann=4,-1,0
  4892.6   0.035       0  4918.5    0.07       0  4992.9    0.07       0
  4996.9    0.07       0
Bank Sta=4992.9,4996.9
Exp/Cntr=0.3,0.1