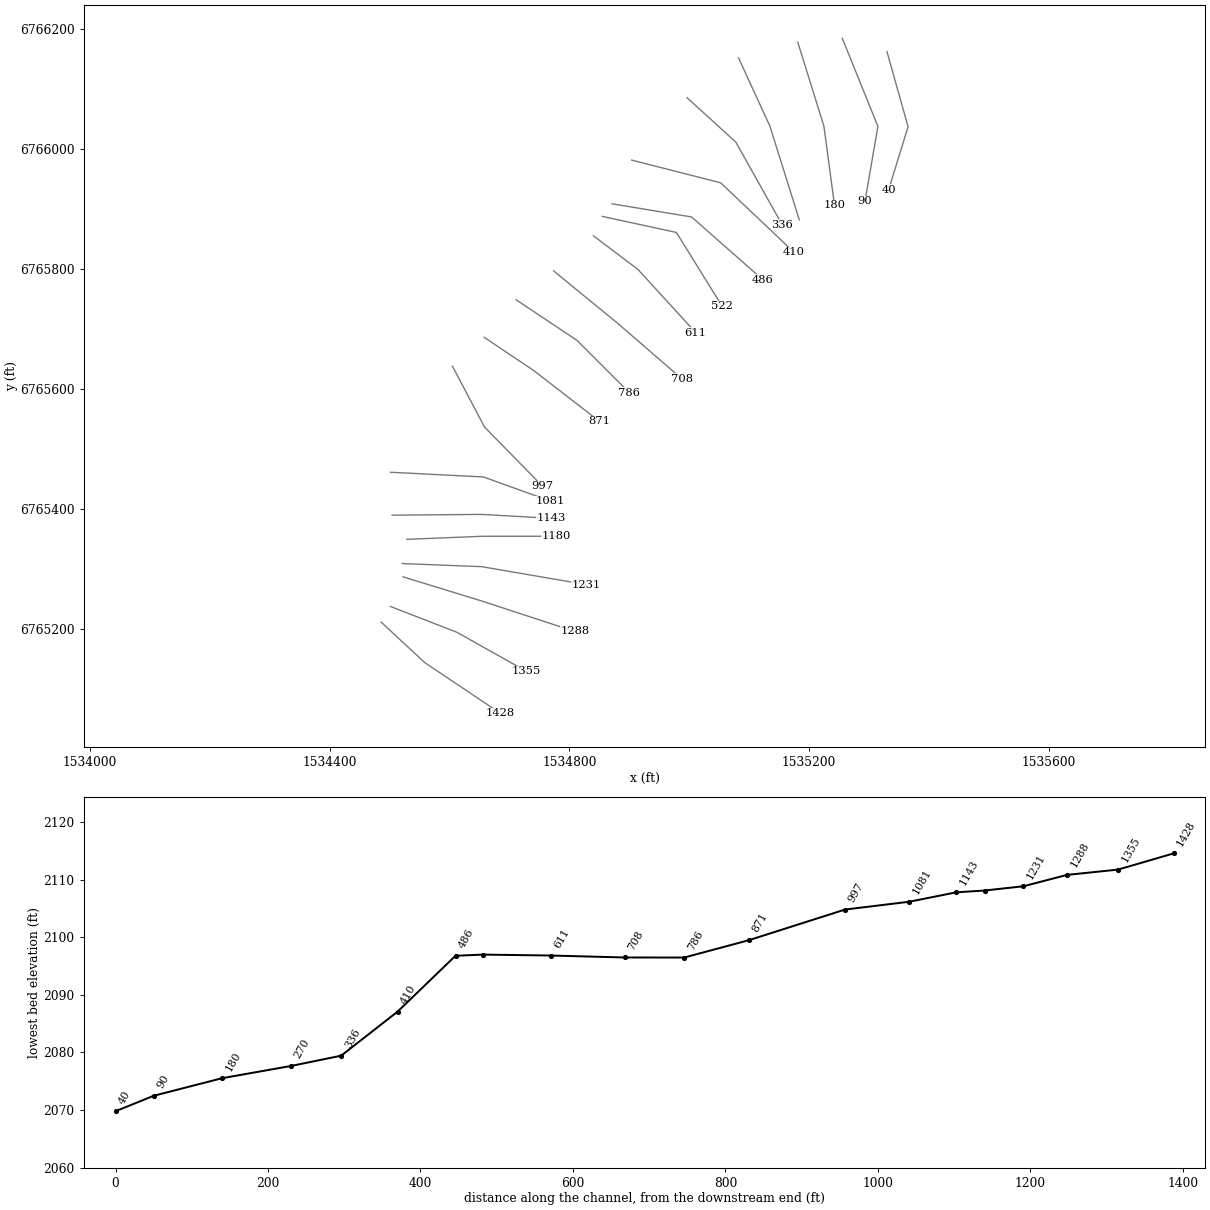
HEC-RAS study Elm 82.prj: Elm 82 Base Level Engineering

--- Elm 82.g01 (geometry) --- (continued)

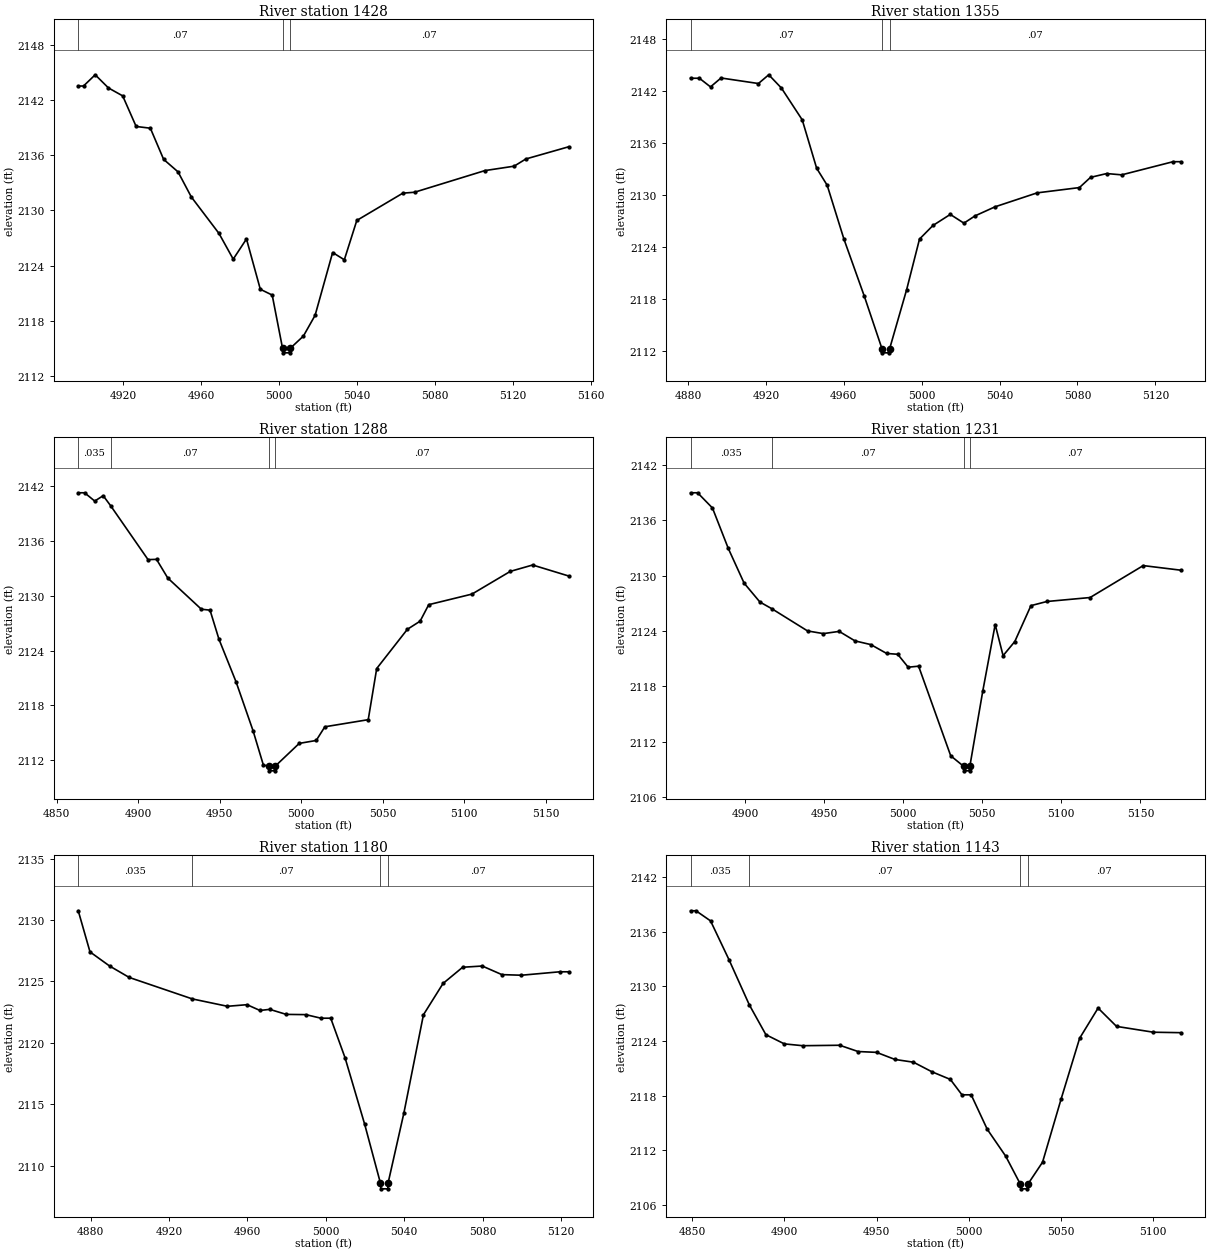
Type RM Length L Ch R = 1,1428,73,73,73
BEGIN DESCRIPTION:
Elm 82 1427.84
END DESCRIPTION:
XS GIS Cut Line= 3
      1534486.01      6765211.09      1534558.91      6765143.39
      1534685.19      6765058.77
#Sta/Elev= 30
  4896.9 2143.50  4899.6 2143.50  4905.6 2144.72  4912.4 2143.29  4919.7 2142.43
  4926.6 2139.11  4933.9 2138.92  4940.7 2135.54  4948.1 2134.18  4954.9 2131.46
  4969.1 2127.50  4976.4 2124.71  4983.2 2126.90  4990.3 2121.44  4996.4 2120.81
  5001.7 2115.04  5002.0 2114.54  5005.5 2114.54  5005.7 2115.04  5012.4 2116.36
  5018.4 2118.61  5027.4 2125.43  5033.4 2124.64  5039.8 2128.91  5063.4 2131.87
  5069.4 2131.97  5105.5 2134.32  5120.5 2134.80  5126.5 2135.58  5148.4 2136.90
#Mann=3,-1,0
  4896.9    0.07       0  5001.7    0.07       0  5005.7    0.07       0
Bank Sta=5001.7,5005.7
Exp/Cntr=0.3,0.1

Type RM Length L Ch R = 1,1355,67,67,67
BEGIN DESCRIPTION:
Elm 82 1354.77
END DESCRIPTION:
XS GIS Cut Line= 3
      1534501.59      6765237.15      1534612.30      6765194.17
      1534728.20      6765129.05
#Sta/Elev= 30
  4881.4 2143.45  4885.9 2143.45  4891.6 2142.45  4897.0 2143.48  4916.2 2142.84
  4921.5 2143.85  4928.0 2142.32  4938.7 2138.64  4946.1 2133.05  4951.5 2131.09
  4960.1 2124.87  4970.6 2118.25  4979.6 2112.23  4979.9 2111.73  4983.4 2111.73
  4983.6 2112.23  4992.3 2119.03  4998.9 2124.87  5005.8 2126.44  5014.7 2127.72
  5021.7 2126.71  5027.4 2127.55  5037.7 2128.60  5059.3 2130.21  5081.0 2130.82
  5086.7 2132.00  5095.0 2132.44  5102.7 2132.29  5129.1 2133.81  5133.1 2133.81
#Mann=3,-1,0
  4881.4    0.07       0  4979.6    0.07       0  4983.6    0.07       0
Bank Sta=4979.6,4983.6
Exp/Cntr=0.3,0.1

Type RM Length L Ch R = 1,1288,57,57,57
BEGIN DESCRIPTION:
Elm 82 1287.54
END DESCRIPTION:
XS GIS Cut Line= 3
      1534522.49      6765286.61      1534653.96      6765246.25
      1534808.92      6765195.47
#Sta/Elev= 30
  4863.3 2141.30  4867.2 2141.30  4873.4 2140.39  4878.6 2140.98  4883.2 2139.87
  4906.1 2133.97  4911.3 2134.00  4918.2 2131.95  4938.8 2128.53  4944.1 2128.43
  4949.6 2125.23  4960.1 2120.55  4970.5 2115.20  4976.8 2111.45  4980.0 2111.31
  4980.3 2110.81  4983.8 2110.81  4984.0 2111.31  4998.8 2113.82  5009.2 2114.14
  5014.5 2115.64  5041.1 2116.42  5046.3 2122.03  5065.1 2126.33  5072.9 2127.22
  5078.2 2129.03  5104.7 2130.19  5128.2 2132.68  5141.9 2133.38  5163.9 2132.18
#Mann=4,-1,0
  4863.3   0.035       0  4883.2    0.07       0  4980.0    0.07       0
  4984.0    0.07       0
Bank Sta=4980,4984
Exp/Cntr=0.3,0.1

Type RM Length L Ch R = 1,1231,51,51,51
BEGIN DESCRIPTION:
Elm 82 1230.64
END DESCRIPTION:
XS GIS Cut Line= 3
      1534521.19      6765308.75      1534653.96      6765303.54
      1534828.44      6765273.60
#Sta/Elev= 30
  4865.7 2138.97  4870.1 2138.97  4879.5 2137.32  4889.5 2132.94  4899.5 2129.18
  4909.5 2127.13  4917.0 2126.41  4939.6 2124.00  4949.6 2123.71  4959.6 2123.95
  4969.6 2122.92  4979.6 2122.52  4989.6 2121.56  4996.6 2121.47  5003.2 2120.07
  5009.8 2120.18  5030.1 2110.47  5038.2 2109.34  5038.5 2108.84  5042.0 2108.84
  5042.2 2109.34  5050.4 2117.52  5058.2 2124.69  5063.2 2121.32  5070.6 2122.85
  5080.8 2126.74  5090.9 2127.19  5118.2 2127.62  5151.8 2131.08  5175.6 2130.58
#Mann=4,-1,0
  4865.7   0.035       0  4917.0    0.07       0  5038.2    0.07       0
  5042.2    0.07       0
Bank Sta=5038.2,5042.2
Exp/Cntr=0.3,0.1

Type RM Length L Ch R = 1,1180,37,37,37
BEGIN DESCRIPTION:
Elm 82 1179.62
END DESCRIPTION:
XS GIS Cut Line= 3
      1534528.98      6765349.12      1534655.27      6765354.32
      1534778.97      6765354.32
#Sta/Elev= 28
  4873.7 2130.75  4879.7 2127.40  4889.7 2126.25  4899.7 2125.32  4931.9 2123.57
  4949.8 2122.97  4959.8 2123.10  4966.4 2122.63  4971.4 2122.72  4979.8 2122.31
  4989.8 2122.29  4997.5 2122.00  5002.5 2122.00  5009.8 2118.78  5019.8 2113.37
  5027.8 2108.60  5028.1 2108.10  5031.6 2108.10  5031.8 2108.60  5039.8 2114.26
  5049.8 2122.28  5059.8 2124.83  5069.8 2126.15  5079.8 2126.25  5089.8 2125.55
  5099.8 2125.50  5119.3 2125.78  5123.8 2125.78
#Mann=4,-1,0
  4873.7   0.035       0  4931.9    0.07       0  5027.8    0.07       0
  5031.8    0.07       0
Bank Sta=5027.8,5031.8
Exp/Cntr=0.3,0.1

Type RM Length L Ch R = 1,1143,62,62,62
BEGIN DESCRIPTION:
Elm 82 1143.29
END DESCRIPTION:
XS GIS Cut Line= 3
      1534504.24      6765389.48      1534652.66      6765390.78
      1534769.85      6765384.27
#Sta/Elev= 30
  4849.2 2138.31  4852.1 2138.31  4860.0 2137.20  4870.0 2132.94  4881.0 2127.99
  4890.0 2124.71  4900.0 2123.70  4910.0 2123.50  4930.0 2123.55  4940.0 2122.86
  4950.0 2122.77  4960.0 2121.99  4970.0 2121.69  4980.0 2120.64  4990.0 2119.80
  4996.3 2118.11  5001.3 2118.11  5010.0 2114.33  5020.0 2111.38  5028.0 2108.29
  5028.3 2107.79  5031.8 2107.79  5032.0 2108.29  5040.0 2110.72  5050.0 2117.61
  5060.1 2124.32  5070.1 2127.63  5080.1 2125.62  5100.1 2124.98  5115.0 2124.93
#Mann=4,-1,0
  4849.2   0.035       0  4881.0    0.07       0  5028.0    0.07       0
  5032.0    0.07       0
Bank Sta=5028,5032
Exp/Cntr=0.3,0.1

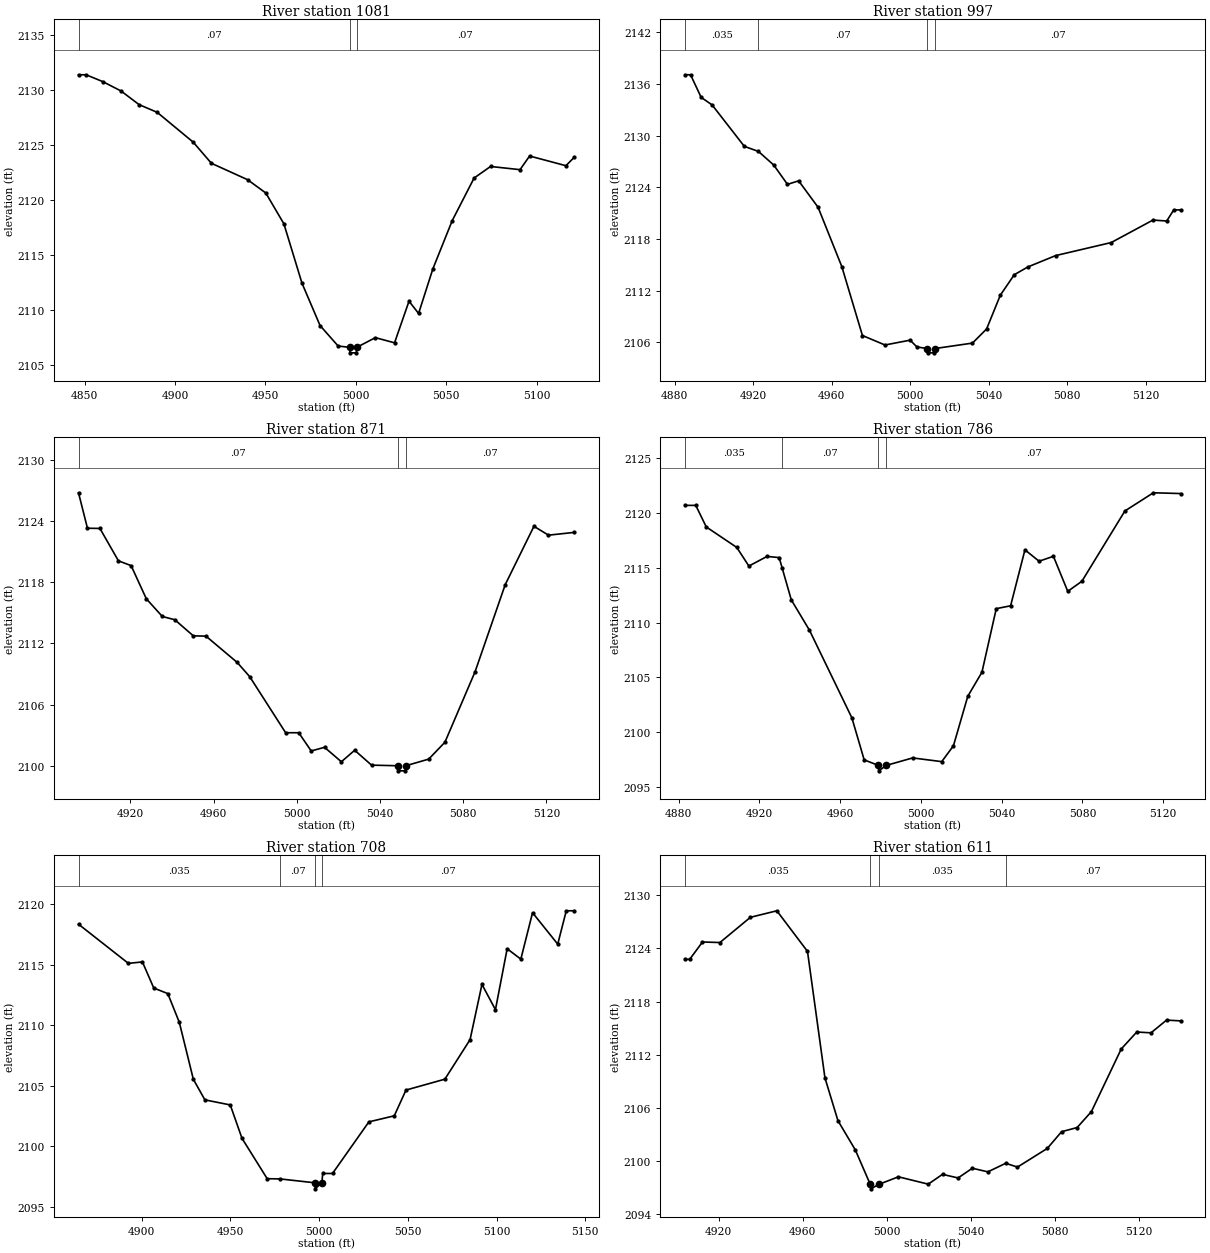
Type RM Length L Ch R = 1,1081,84,84,84
BEGIN DESCRIPTION:
Elm 82 1080.56
END DESCRIPTION:
XS GIS Cut Line= 3
      1534501.58      6765461.10      1534656.57      6765453.28
      1534768.43      6765412.96
#Sta/Elev= 30
  4846.6 2131.41  4850.8 2131.41  4860.0 2130.79  4870.1 2129.94  4880.1 2128.70
  4890.1 2128.00  4910.1 2125.28  4920.1 2123.37  4940.1 2121.88  4950.2 2120.67
  4960.2 2117.87  4970.2 2112.48  4980.2 2108.63  4990.2 2106.77  4996.5 2106.65
  4996.8 2106.15  5000.3 2106.15  5000.5 2106.65  5010.8 2107.53  5021.4 2107.06
  5029.4 2110.84  5034.7 2109.73  5042.6 2113.78  5053.3 2118.16  5065.4 2122.03
  5074.5 2123.08  5090.8 2122.79  5096.1 2124.03  5116.2 2123.15  5120.7 2123.90
#Mann=3,-1,0
  4846.6    0.07       0  4996.5    0.07       0  5000.5    0.07       0
Bank Sta=4996.5,5000.5
Exp/Cntr=0.3,0.1

Type RM Length L Ch R = 1,997,126,126,126
BEGIN DESCRIPTION:
Elm 82 997.124
END DESCRIPTION:
XS GIS Cut Line= 3
      1534605.01      6765637.98      1534658.54      6765536.54
      1534755.00      6765438.00
#Sta/Elev= 30
  4885.3 2137.05  4888.1 2137.05  4893.5 2134.43  4899.1 2133.55  4915.5 2128.75
  4922.7 2128.16  4930.5 2126.58  4937.5 2124.34  4943.2 2124.75  4953.1 2121.68
  4965.2 2114.80  4975.7 2106.81  4987.2 2105.71  5000.0 2106.27  5003.5 2105.48
  5008.7 2105.30  5008.9 2104.80  5012.4 2104.80  5012.7 2105.30  5031.8 2105.93
  5039.0 2107.57  5046.0 2111.49  5053.1 2113.86  5060.1 2114.77  5074.2 2116.08
  5102.5 2117.59  5123.8 2120.20  5130.8 2120.09  5134.4 2121.38  5137.9 2121.38
#Mann=4,-1,0
  4885.3   0.035       0  4922.7    0.07       0  5008.7    0.07       0
  5012.7    0.07       0
Bank Sta=5008.7,5012.7
Exp/Cntr=0.3,0.1

Type RM Length L Ch R = 1,871,85,85,85
BEGIN DESCRIPTION:
Elm 82 871.47
END DESCRIPTION:
XS GIS Cut Line= 3
      1534657.90      6765686.33      1534741.20      6765630.37
      1534850.30      6765545.95
#Sta/Elev= 30
  4895.0 2126.78  4899.3 2123.30  4905.3 2123.28  4914.2 2120.10  4920.3 2119.63
  4927.6 2116.38  4935.3 2114.64  4941.3 2114.32  4950.2 2112.74  4956.3 2112.71
  4971.3 2110.13  4977.3 2108.74  4994.6 2103.23  5000.9 2103.23  5006.9 2101.44
  5013.3 2101.80  5021.4 2100.38  5027.8 2101.51  5035.9 2100.05  5048.4 2099.99
  5048.7 2099.49  5052.2 2099.49  5052.4 2099.99  5063.4 2100.64  5071.2 2102.30
  5085.7 2109.22  5100.2 2117.77  5114.0 2123.49  5121.0 2122.62  5133.3 2122.89
#Mann=3,-1,0
  4895.0    0.07       0  5048.4    0.07       0  5052.4    0.07       0
Bank Sta=5048.4,5052.4
Exp/Cntr=0.3,0.1

Type RM Length L Ch R = 1,786,78,78,78
BEGIN DESCRIPTION:
Elm 82 785.87
END DESCRIPTION:
XS GIS Cut Line= 3
      1534711.26      6765748.86      1534812.82      6765681.15
      1534900.03      6765593.93
#Sta/Elev= 30
  4883.2 2120.71  4888.5 2120.71  4893.7 2118.74  4908.8 2116.87  4914.8 2115.17
  4923.8 2116.05  4929.8 2115.94  4931.3 2114.98  4935.8 2112.08  4944.8 2109.31
  4965.8 2101.31  4971.9 2097.47  4978.9 2096.97  4979.1 2096.47  4982.9 2096.97
  4995.9 2097.65  5010.3 2097.31  5016.1 2098.76  5023.2 2103.28  5030.2 2105.47
  5037.3 2111.28  5044.4 2111.54  5051.5 2116.65  5058.5 2115.61  5065.6 2116.06
  5072.7 2112.86  5079.7 2113.78  5101.0 2120.20  5115.1 2121.86  5128.6 2121.79
#Mann=4,-1,0
  4883.2   0.035       0  4931.3    0.07       0  4978.9    0.07       0
  4982.9    0.07       0
Bank Sta=4978.9,4982.9
Exp/Cntr=0.3,0.1

Type RM Length L Ch R = 1,708,97,97,97
BEGIN DESCRIPTION:
Elm 82 708.02
END DESCRIPTION:
XS GIS Cut Line= 3
      1534773.72      6765797.06      1534880.53      6765709.79
      1534987.33      6765617.32
#Sta/Elev= 30
  4864.5 2118.37  4892.6 2115.13  4900.5 2115.25  4906.9 2113.09  4914.8 2112.63
  4921.3 2110.25  4929.2 2105.54  4935.7 2103.84  4950.0 2103.42  4956.6 2100.66
  4970.8 2097.32  4978.1 2097.30  4997.6 2096.98  4997.8 2096.48  5001.6 2096.98
  5002.1 2097.75  5007.6 2097.75  5028.1 2102.02  5042.4 2102.52  5049.0 2104.65
  5070.9 2105.55  5085.1 2108.82  5091.8 2113.39  5099.4 2111.30  5106.0 2116.34
  5113.7 2115.48  5120.3 2119.32  5134.5 2116.72  5139.3 2119.48  5143.7 2119.48
#Mann=4,-1,0
  4864.5   0.035       0  4978.1    0.07       0  4997.6    0.07       0
  5001.6    0.07       0
Bank Sta=4997.6,5001.6
Exp/Cntr=0.3,0.1

Type RM Length L Ch R = 1,611,89,89,89
BEGIN DESCRIPTION:
Elm 82 610.86
END DESCRIPTION:
XS GIS Cut Line= 3
      1534840.18      6765855.61      1534914.38      6765799.64
      1535010.93      6765694.08
#Sta/Elev= 30
  4904.0 2122.77  4906.2 2122.77  4912.3 2124.73  4920.6 2124.67  4935.1 2127.52
  4947.7 2128.26  4962.3 2123.67  4970.6 2109.38  4976.8 2104.53  4985.1 2101.21
  4992.2 2097.32  4992.5 2096.82  4996.2 2097.32  5005.6 2098.18  5019.8 2097.35
  5026.6 2098.46  5034.0 2098.05  5040.8 2099.15  5048.2 2098.74  5056.7 2099.71
  5062.3 2099.28  5076.5 2101.39  5083.3 2103.28  5090.7 2103.75  5097.5 2105.55
  5111.7 2112.63  5119.1 2114.55  5125.9 2114.46  5133.3 2115.90  5140.0 2115.81
#Mann=4,-1,0
  4904.0   0.035       0  4992.2   0.035       0  4996.2   0.035       0
  5056.7    0.07       0
Bank Sta=4992.2,4996.2
Exp/Cntr=0.3,0.1

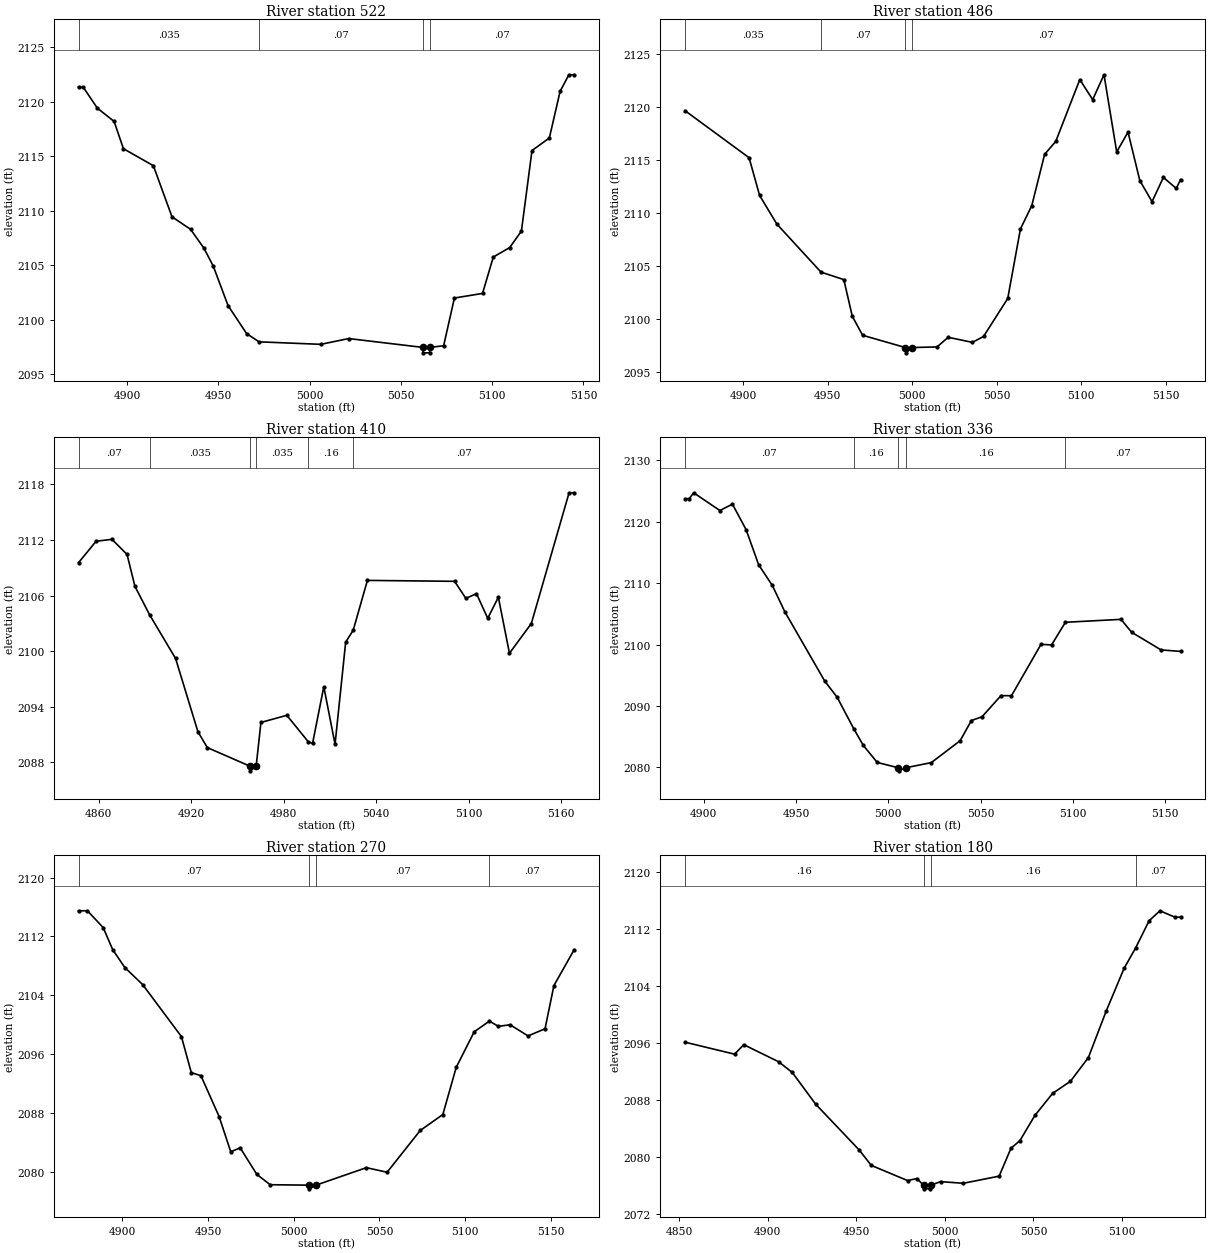
Type RM Length L Ch R = 1,522,36,36,36
BEGIN DESCRIPTION:
Elm 82 521.728
END DESCRIPTION:
XS GIS Cut Line= 3
      1534854.96      6765888.01      1534978.69      6765861.18
      1535055.00      6765738.00
#Sta/Elev= 30
  4873.4 2121.35  4876.0 2121.35  4883.7 2119.43  4892.9 2118.21  4898.0 2115.71
  4914.4 2114.15  4924.6 2109.46  4934.8 2108.31  4942.1 2106.58  4947.2 2104.94
  4955.3 2101.32  4965.5 2098.74  4972.3 2097.99  5006.1 2097.76  5021.4 2098.29
  5061.9 2097.48  5062.2 2096.98  5065.7 2096.98  5065.9 2097.48  5073.4 2097.63
  5079.3 2102.01  5094.7 2102.43  5100.6 2105.77  5109.6 2106.64  5116.0 2108.15
  5121.8 2115.54  5131.3 2116.69  5137.2 2120.97  5142.0 2122.49  5144.9 2122.49
#Mann=4,-1,0
  4873.4   0.035       0  4972.3    0.07       0  5061.9    0.07       0
  5065.9    0.07       0
Bank Sta=5061.9,5065.9
Exp/Cntr=0.3,0.1

Type RM Length L Ch R = 1,486,76,76,76
BEGIN DESCRIPTION:
Elm 82 4122
END DESCRIPTION:
XS GIS Cut Line= 3
      1534871.44      6765909.01      1535003.94      6765887.06
      1535123.08      6765782.23
#Sta/Elev= 30
  4865.7 2119.67  4903.6 2115.22  4909.8 2111.66  4920.0 2108.95  4946.1 2104.41
  4959.6 2103.70  4964.6 2100.24  4970.7 2098.44  4996.0 2097.28  4996.3 2096.78
  5000.0 2097.28  5014.7 2097.34  5021.3 2098.25  5035.6 2097.77  5042.2 2098.33
  5056.5 2101.92  5064.0 2108.49  5070.7 2110.69  5078.3 2115.54  5084.9 2116.77
  5099.1 2122.61  5106.7 2120.71  5113.4 2123.06  5120.9 2115.77  5127.6 2117.64
  5134.6 2113.05  5141.8 2111.07  5148.5 2113.36  5156.1 2112.32  5158.7 2113.16
#Mann=4,-1,0
  4865.7   0.035       0  4946.1    0.07       0  4996.0    0.07       0
  5000.0    0.07       0
Bank Sta=4996,5000
Exp/Cntr=0.3,0.1

Type RM Length L Ch R = 1,410,74,74,74
BEGIN DESCRIPTION:
Elm 82 4121
END DESCRIPTION:
XS GIS Cut Line= 3
      1534903.99      6765981.92      1535052.45      6765944.09
      1535174.82      6765828.26
#Sta/Elev= 30
  4846.8 2109.54  4858.2 2111.85  4868.5 2112.06  4878.3 2110.43  4883.4 2107.00
  4892.9 2103.93  4909.8 2099.21  4924.3 2091.31  4930.4 2089.60  4958.1 2087.59
  4958.3 2087.09  4962.1 2087.59  4965.2 2092.31  4982.0 2093.08  4995.8 2090.25
  4998.7 2090.04  5006.0 2096.16  5013.3 2089.96  5020.2 2100.97  5025.1 2102.26
  5034.3 2107.63  5090.9 2107.53  5098.2 2105.69  5105.1 2106.20  5112.4 2103.54
  5119.3 2105.81  5126.5 2099.77  5140.7 2102.98  5165.2 2117.08  5168.5 2117.08
#Mann=6,-1,0
  4846.8    0.07       0  4892.9   0.035       0  4958.1    0.07       0
  4962.1   0.035       0  4995.8    0.16       0  5025.1    0.07       0
Bank Sta=4958.1,4962.1
Exp/Cntr=0.3,0.1

Type RM Length L Ch R = 1,336,66,66,66
BEGIN DESCRIPTION:
Elm 82 4120
END DESCRIPTION:
XS GIS Cut Line= 3
      1534996.41      6766086.10      1535077.81      6766011.97
      1535155.24      6765873.90
#Sta/Elev= 30
  4889.9 2123.77  4892.2 2123.77  4894.6 2124.74  4908.8 2121.85  4915.6 2122.89
  4923.0 2118.73  4929.8 2113.01  4937.2 2109.64  4944.0 2105.34  4965.6 2094.05
  4972.3 2091.43  4981.3 2086.29  4986.5 2083.57  4994.0 2080.81  5005.4 2079.94
  5005.6 2079.44  5009.4 2079.94  5023.3 2080.78  5038.9 2084.35  5045.0 2087.63
  5050.8 2088.26  5061.0 2091.69  5066.7 2091.68  5082.7 2100.05  5088.4 2099.95
  5095.9 2103.64  5126.0 2104.12  5131.8 2102.01  5147.7 2099.14  5158.3 2098.90
#Mann=5,-1,0
  4889.9    0.07       0  4981.3    0.16       0  5005.4    0.07       0
  5009.4    0.16       0  5095.9    0.07       0
Bank Sta=5005.4,5009.4
Exp/Cntr=0.3,0.1

Type RM Length L Ch R = 1,270,90,90,90
BEGIN DESCRIPTION:
Elm 82 4119
END DESCRIPTION:
XS GIS Cut Line= 3
      1535082.35      6766152.50      1535134.75      6766038.46
      1535183.70      6765882.35
#Sta/Elev= 30
  4874.5 2115.49  4879.7 2115.49  4888.9 2113.20  4894.4 2110.22  4901.5 2107.77
  4911.9 2105.45  4934.5 2098.38  4940.3 2093.46  4945.9 2093.05  4956.5 2087.49
  4963.3 2082.69  4968.8 2083.23  4978.5 2079.62  4986.3 2078.21  5009.0 2078.15
  5009.2 2077.65  5013.0 2078.15  5042.4 2080.53  5054.5 2079.91  5073.8 2085.59
  5087.0 2087.76  5094.8 2094.18  5105.3 2099.02  5114.2 2100.48  5119.4 2099.76
  5126.2 2099.98  5136.7 2098.46  5146.6 2099.43  5151.8 2105.32  5163.6 2110.19
#Mann=4,-1,0
  4874.5    0.07       0  5009.0    0.07       0  5013.0    0.07       0
  5114.2    0.07       0
Bank Sta=5009,5013
Exp/Cntr=0.3,0.1

Type RM Length L Ch R = 1,180,90,90,90
BEGIN DESCRIPTION:
Elm 82 4118
END DESCRIPTION:
XS GIS Cut Line= 3
      1535181.32      6766178.51      1535224.83      6766038.31
      1535242.51      6765906.39
#Sta/Elev= 30
  4853.2 2096.12  4881.2 2094.44  4886.4 2095.77  4906.1 2093.37  4913.8 2091.87
  4927.0 2087.42  4951.6 2080.99  4958.4 2078.83  4978.9 2076.70  4984.2 2076.99
  4987.9 2076.04  4988.1 2075.54  4991.6 2075.54  4991.9 2076.04  4997.5 2076.55
  5010.4 2076.32  5030.6 2077.32  5037.3 2081.24  5042.3 2082.29  5050.8 2085.84
  5060.8 2088.93  5070.9 2090.64  5081.0 2093.96  5091.1 2100.51  5101.2 2106.50
  5107.8 2109.40  5115.3 2113.16  5121.4 2114.56  5129.8 2113.67  5133.1 2113.67
#Mann=4,-1,0
  4853.2    0.16       0  4987.9    0.07       0  4991.9    0.16       0
  5107.8    0.07       0
Bank Sta=4987.9,4991.9
Exp/Cntr=0.3,0.1

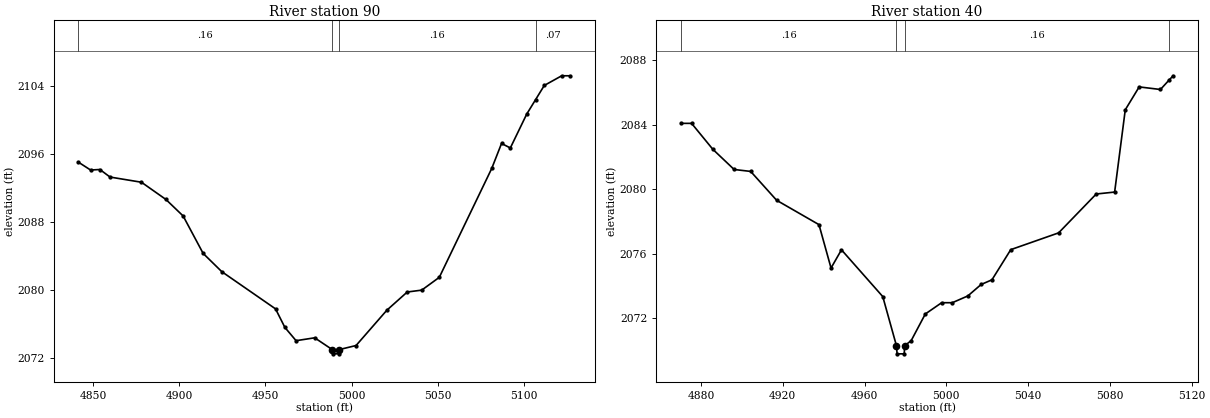
Type RM Length L Ch R = 1,90,50,50,50
BEGIN DESCRIPTION:
Elm 82 4115
END DESCRIPTION:
XS GIS Cut Line= 3
      1535255.51      6766185.10      1535314.92      6766038.15
      1535293.29      6765913.01
#Sta/Elev= 30
  4841.5 2095.08  4848.6 2094.15  4854.0 2094.21  4859.9 2093.32  4878.1 2092.71
  4892.3 2090.68  4902.3 2088.73  4913.9 2084.32  4924.7 2082.17  4955.9 2077.78
  4961.3 2075.60  4967.8 2074.03  4978.6 2074.37  4988.8 2072.98  4989.1 2072.48
  4992.6 2072.48  4992.8 2072.98  5002.6 2073.46  5020.5 2077.63  5032.3 2079.77
  5040.7 2079.99  5050.9 2081.50  5081.3 2094.33  5087.0 2097.28  5092.1 2096.75
  5101.6 2100.74  5106.7 2102.43  5111.8 2104.12  5121.9 2105.26  5127.0 2105.26
#Mann=4,-1,0
  4841.5    0.16       0  4988.8    0.07       0  4992.8    0.16       0
  5106.7    0.07       0
Bank Sta=4988.8,4992.8
Exp/Cntr=0.3,0.1

Type RM Length L Ch R = 1,40,0,0,0
BEGIN DESCRIPTION:
Elm 82 4117
END DESCRIPTION:
XS GIS Cut Line= 3
      1535329.99      6766163.03      1535365.24      6766037.57
      1535332.65      6765932.11
#Sta/Elev= 30
  4870.2 2084.09  4875.4 2084.09  4885.8 2082.48  4896.2 2081.23  4904.3 2081.11
  4917.0 2079.32  4937.7 2077.81  4943.6 2075.12  4948.7 2076.25  4968.9 2073.35
  4975.6 2070.30  4975.9 2069.80  4979.4 2069.80  4979.6 2070.30  4982.8 2070.62
  4989.7 2072.27  4997.7 2072.97  5002.9 2072.97  5010.5 2073.39  5017.0 2074.10
  5022.3 2074.39  5031.5 2076.26  5054.9 2077.30  5073.3 2079.71  5082.3 2079.83
  5087.5 2084.93  5094.3 2086.35  5104.7 2086.19  5108.9 2086.77  5110.9 2087.04
#Mann=4,-1,0
  4870.2    0.16       0  4975.6    0.07       0  4979.6    0.16       0
  5108.9    0.07       0
Bank Sta=4975.6,4979.6
Exp/Cntr=0.3,0.1

Chan Stop Cuts=-1