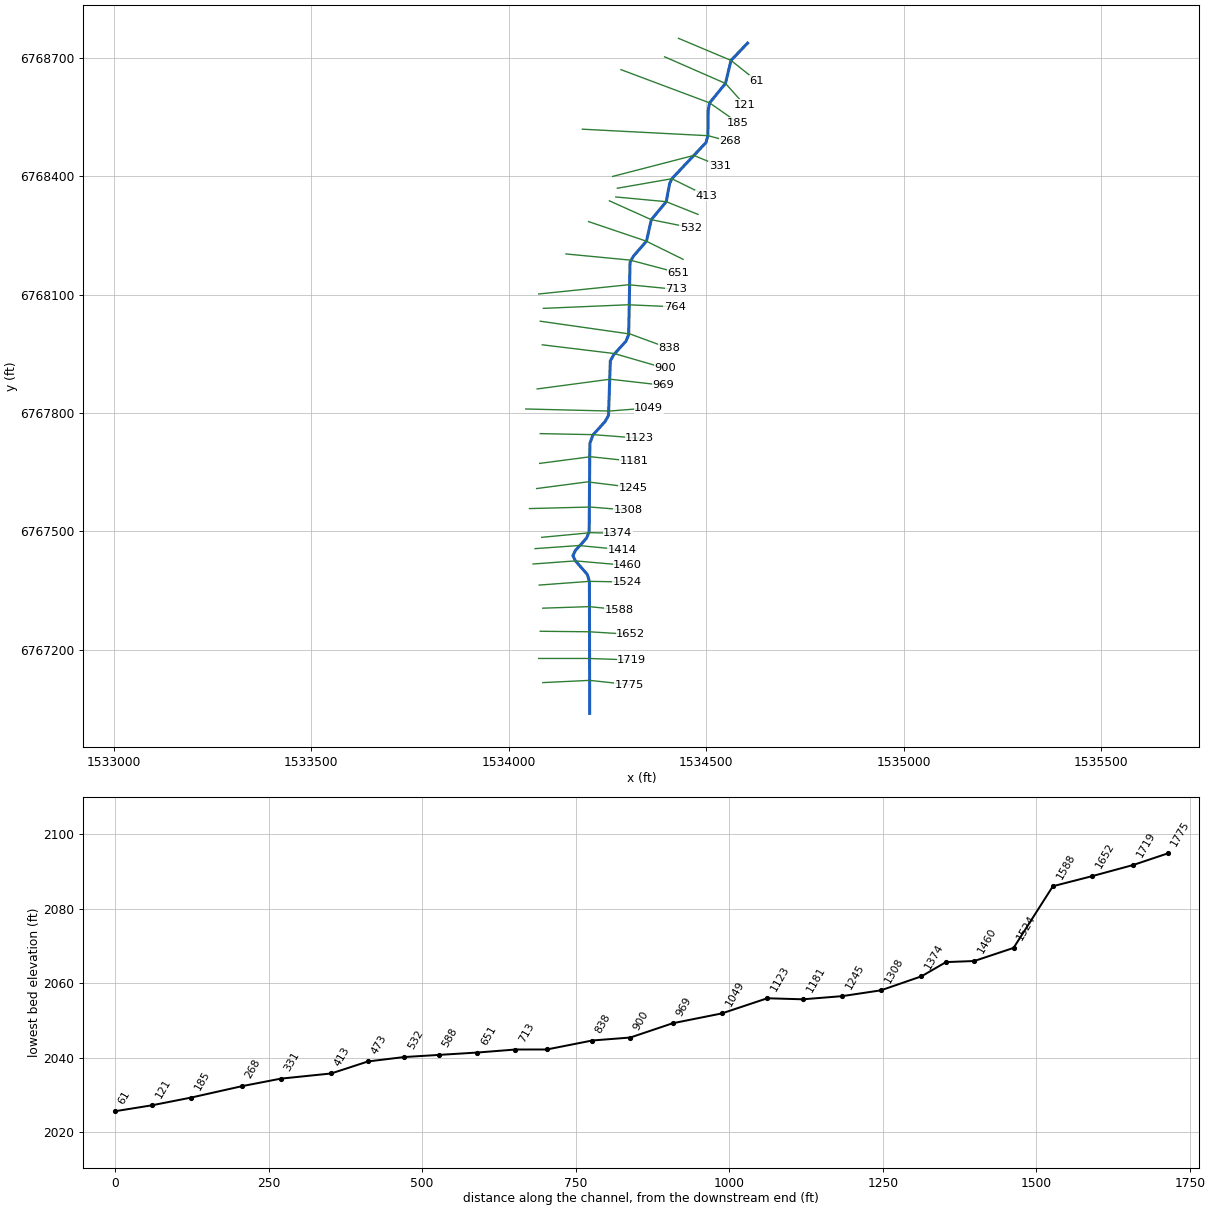
--- Elm 83.prj (project) ---

Proj Title=Elm 83 Base Level Engineering
Current Plan=p01
Default Exp/Contr=0.3,0.1
English Units
Geom File=g01
Flow File=f01
Plan File=p01
BEGIN DESCRIPTION:
Elm 83
END DESCRIPTION:

--- Elm 83.p01 (plan) ---

Plan Title=Multiple Run
Short Identifier=Multiple
Geom File=g01
Flow File=f01
Subcritical Flow
K Sum by GR= 0
Std Step Tol= 0.01
Critical Tol= 0.01
Num of Std Step Trials= 20
Max Error Tol= 0.3
Flow Tol Ratio= 0.001
Split Flow NTrial= 30
Split Flow Tol= 0.02
Split Flow Ratio= 0.02
Log Output Level= 0
Friction Slope Method= 1
Unsteady Friction Slope Method= 2
Unsteady Bridges Friction Slope Method= 1
Parabolic Critical Depth
Global Vel Dist=  1 , 1 , 1
Global Log Level= 0
CheckData=True
Encroach Param= -1, 0, 0, 0
BEGIN DESCRIPTION:
Multiple Run
END DESCRIPTION:

--- Elm 83.f01 (steady flow) ---

Flow Title=Multiple
Number of Profiles=7
Profile Names=10-year,25-year,50-year,1pct_min,100-year,1pct_plu,500-year
River Rch & RM= Elm 83,Reach-1,1775
      52      66      76      55      88     121     119
Boundary for River Rch & Prof#=Elm 83,Reach-1,1
Up Type=0
Dn Type=3
Dn Slope=0.005
Boundary for River Rch & Prof#=Elm 83,Reach-1,2
Up Type=0
Dn Type=3
Dn Slope=0.005
Boundary for River Rch & Prof#=Elm 83,Reach-1,3
Up Type=0
Dn Type=3
Dn Slope=0.005
Boundary for River Rch & Prof#=Elm 83,Reach-1,4
Up Type=0
Dn Type=3
Dn Slope=0.005
Boundary for River Rch & Prof#=Elm 83,Reach-1,5
Up Type=0
Dn Type=3
Dn Slope=0.005
Boundary for River Rch & Prof#=Elm 83,Reach-1,6
Up Type=0
Dn Type=3
Dn Slope=0.005
Boundary for River Rch & Prof#=Elm 83,Reach-1,7
Up Type=0
Dn Type=3
Dn Slope=0.005

--- Elm 83.g01 (geometry) ---

Geom Title=Existing Conditions

River Reach=Elm 83,Reach-1
Reach XY= 30
      1534205.00      6767038.00      1534204.34      6767372.84
      1534198.98      6767390.45      1534168.95      6767424.79
      1534162.56      6767438.00      1534168.95      6767451.21
      1534196.55      6767481.81      1534203.62      6767498.44
      1534205.52      6767722.78      1534213.14      6767744.06
      1534244.14      6767778.36      1534252.73      6767793.94
      1534257.27      6767932.06      1534265.86      6767947.64
      1534296.86      6767981.94      1534303.78      6767998.51
      1534307.24      6768182.07      1534315.80      6768197.67
      1534348.88      6768235.82      1534361.08      6768290.20
      1534398.90      6768335.81      1534407.51      6768381.96
      1534413.16      6768394.05      1534499.46      6768485.58
      1534504.47      6768503.22      1534505.23      6768567.90
      1534508.82      6768586.42      1534548.97      6768635.78
      1534562.91      6768694.15      1534605.00      6768738.00

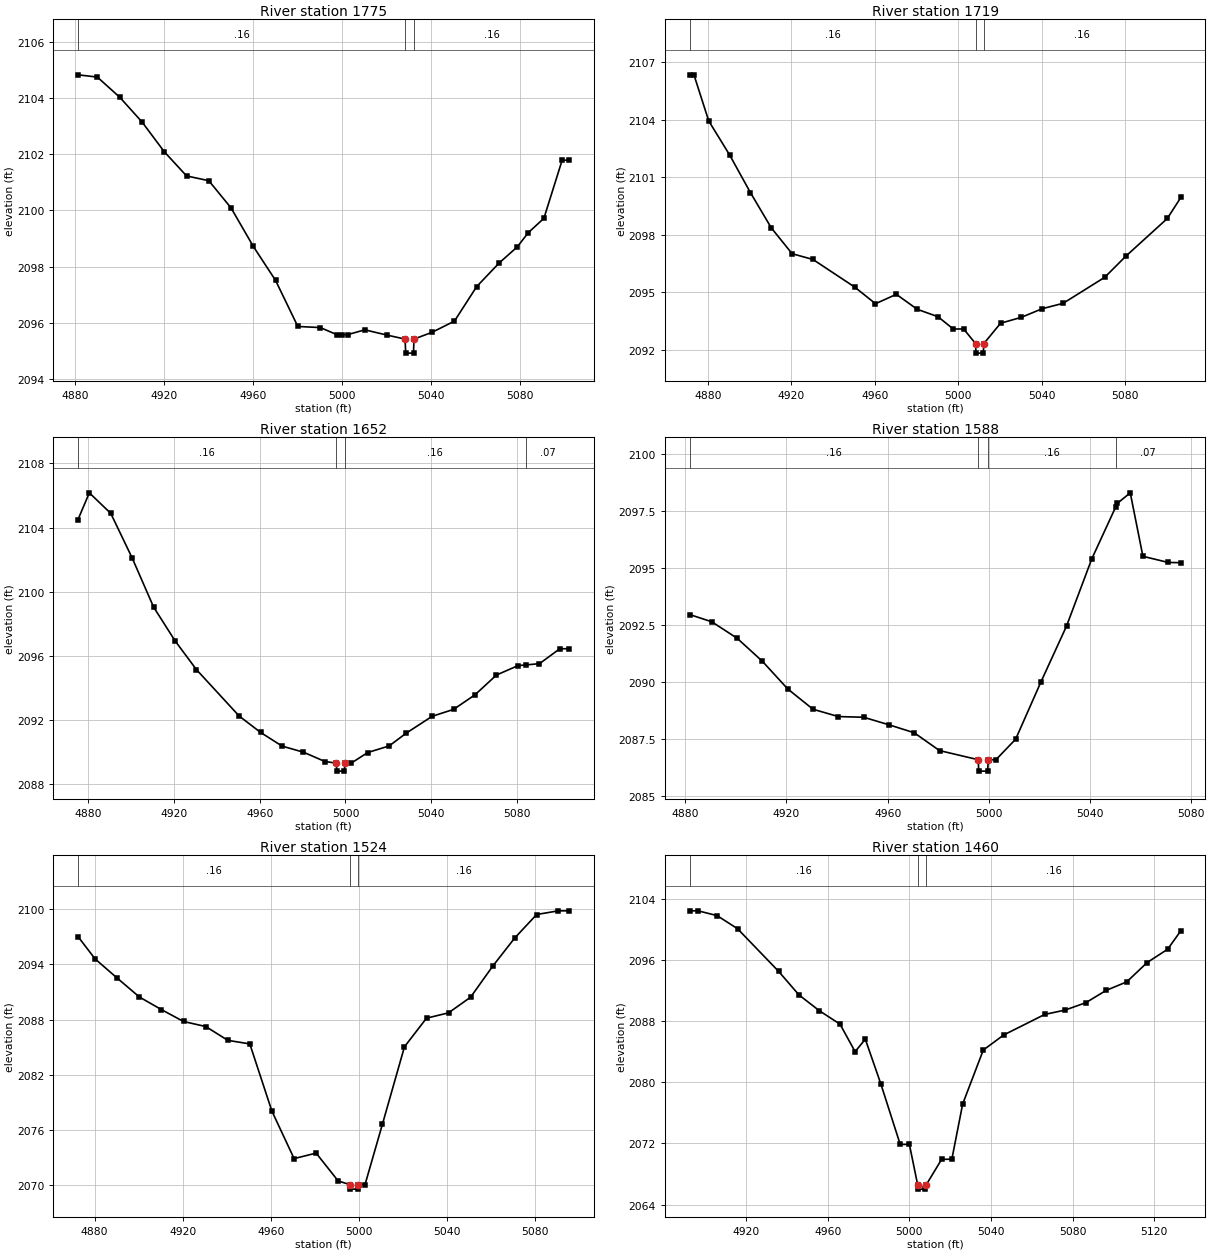
Type RM Length L Ch R = 1,1775,56,56,56
BEGIN DESCRIPTION:
Elm 83 4154
END DESCRIPTION:
XS GIS Cut Line= 3
      1534086.27      6767116.04      1534204.84      6767121.71
      1534306.35      6767110.83
#Sta/Elev= 30
  4881.3 2104.83  4890.0 2104.75  4900.1 2104.03  4910.1 2103.15  4920.1 2102.09
  4930.1 2101.23  4940.1 2101.06  4950.1 2100.09  4960.1 2098.72  4970.1 2097.51
  4980.1 2095.87  4990.2 2095.83  4997.6 2095.58  5000.0 2095.58  5002.6 2095.58
  5010.2 2095.75  5020.3 2095.56  5028.3 2095.42  5028.6 2094.92  5032.1 2094.92
  5032.3 2095.42  5040.4 2095.66  5050.5 2096.06  5060.5 2097.29  5070.6 2098.13
  5078.7 2098.70  5083.7 2099.21  5090.7 2099.72  5098.9 2101.79  5102.1 2101.79
#Mann=3,-1,0
  4881.3    0.16       0  5028.3    0.07       0  5032.3    0.16       0
Bank Sta=5028.3,5032.3
Exp/Cntr=0.3,0.1

Type RM Length L Ch R = 1,1719,67,67,67
BEGIN DESCRIPTION:
Elm 83 4153
END DESCRIPTION:
XS GIS Cut Line= 3
      1534075.83      6767177.24      1534204.73      6767177.24
      1534311.46      6767173.38
#Sta/Elev= 27
  4871.1 2106.35  4873.2 2106.35  4880.3 2103.94  4890.3 2102.17  4900.3 2100.20
  4910.3 2098.36  4920.3 2097.01  4930.3 2096.71  4950.3 2095.27  4960.3 2094.40
  4970.3 2094.89  4980.3 2094.11  4990.3 2093.72  4997.6 2093.08  5002.6 2093.08
  5008.3 2092.32  5008.5 2091.82  5012.0 2091.82  5012.3 2092.32  5020.3 2093.38
  5030.3 2093.69  5040.3 2094.14  5050.3 2094.42  5070.3 2095.78  5080.3 2096.87
  5100.3 2098.85  5106.8 2099.95
#Mann=3,-1,0
  4871.1    0.16       0  5008.3    0.07       0  5012.3    0.16       0
Bank Sta=5008.3,5012.3
Exp/Cntr=0.3,0.1

Type RM Length L Ch R = 1,1652,64,64,64
BEGIN DESCRIPTION:
Elm 83 4151
END DESCRIPTION:
XS GIS Cut Line= 3
      1534079.70      6767246.25      1534204.59      6767244.95
      1534308.89      6767238.44
#Sta/Elev= 29
  4875.1 2104.50  4880.4 2106.17  4890.4 2104.89  4900.4 2102.11  4910.4 2099.05
  4920.4 2096.95  4930.4 2095.15  4950.4 2092.25  4960.4 2091.23  4970.4 2090.38
  4980.4 2090.00  4990.4 2089.42  4995.7 2089.32  4996.0 2088.82  4999.5 2088.82
  4999.7 2089.32  5002.7 2089.32  5010.4 2089.98  5020.4 2090.39  5028.4 2091.19
  5040.5 2092.24  5050.5 2092.67  5060.5 2093.58  5070.5 2094.81  5080.6 2095.40
  5084.2 2095.44  5090.6 2095.52  5100.1 2096.45  5104.5 2096.45
#Mann=4,-1,0
  4875.1    0.16       0  4995.7    0.07       0  4999.7    0.16       0
  5084.2    0.07       0
Bank Sta=4995.7,4999.7
Exp/Cntr=0.3,0.1

Type RM Length L Ch R = 1,1588,64,64,64
BEGIN DESCRIPTION:
Elm 83 4150
END DESCRIPTION:
XS GIS Cut Line= 3
      1534086.23      6767304.84      1534204.47      6767308.75
      1534279.97      6767300.94
#Sta/Elev= 27
  4881.7 2092.97  4890.5 2092.65  4900.5 2091.93  4910.5 2090.92  4920.5 2089.71
  4930.5 2088.82  4940.5 2088.50  4950.5 2088.47  4960.5 2088.14  4970.5 2087.79
  4980.5 2087.01  4995.8 2086.61  4996.0 2086.11  4999.5 2086.11  4999.8 2086.61
  5000.0 2086.61  5002.8 2086.61  5010.6 2087.51  5020.6 2090.02  5030.7 2092.46
  5040.7 2095.41  5050.1 2097.67  5050.8 2097.84  5055.9 2098.30  5060.9 2095.52
  5070.9 2095.25  5075.9 2095.24
#Mann=4,-1,0
  4881.7    0.16       0  4995.8    0.07       0  4999.8    0.16       0
  5050.1    0.07       0
Bank Sta=4995.8,4999.8
Exp/Cntr=0.3,0.1

Type RM Length L Ch R = 1,1524,64,64,64
BEGIN DESCRIPTION:
Elm 83 4149
END DESCRIPTION:
XS GIS Cut Line= 3
      1534077.19      6767363.44      1534204.34      6767372.84
      1534299.83      6767371.25
#Sta/Elev= 29
  4872.5 2097.03  4880.3 2094.59  4890.4 2092.49  4900.4 2090.45  4910.4 2089.08
  4920.4 2087.79  4930.5 2087.24  4940.5 2085.74  4950.5 2085.35  4960.5 2078.05
  4970.6 2072.87  4980.6 2073.47  4990.6 2070.44  4995.8 2070.05  4996.1 2069.55
  4999.6 2069.55  4999.8 2070.05  5000.0 2070.05  5002.8 2070.05  5010.7 2076.62
  5020.7 2085.04  5030.7 2088.15  5040.7 2088.73  5050.7 2090.43  5060.7 2093.79
  5070.7 2096.86  5080.7 2099.43  5090.6 2099.83  5095.5 2099.83
#Mann=3,-1,0
  4872.5    0.16       0  4995.8    0.07       0  4999.8    0.16       0
Bank Sta=4995.8,4999.8
Exp/Cntr=0.3,0.1

Type RM Length L Ch R = 1,1460,46,46,46
BEGIN DESCRIPTION:
Elm 83 1459.66
END DESCRIPTION:
XS GIS Cut Line= 3
      1534061.55      6767416.83      1534168.95      6767424.79
      1534301.44      6767413.12
#Sta/Elev= 30
  4892.3 2102.43  4896.5 2102.43  4905.8 2101.80  4915.8 2100.09  4935.9 2094.52
  4945.9 2091.43  4955.9 2089.36  4966.0 2087.61  4973.4 2084.01  4978.4 2085.64
  4986.0 2079.80  4995.5 2071.88  5000.0 2071.88  5004.1 2066.53  5004.3 2066.03
  5007.8 2066.03  5008.1 2066.53  5015.8 2069.93  5020.8 2069.94  5026.1 2077.16
  5036.2 2084.22  5046.2 2086.19  5066.3 2088.88  5076.3 2089.45  5086.4 2090.41
  5096.4 2092.02  5106.5 2093.14  5116.5 2095.67  5126.5 2097.40  5133.0 2099.82
#Mann=3,-1,0
  4892.3    0.16       0  5004.1    0.07       0  5008.1    0.16       0
Bank Sta=5004.1,5008.1
Exp/Cntr=0.3,0.1

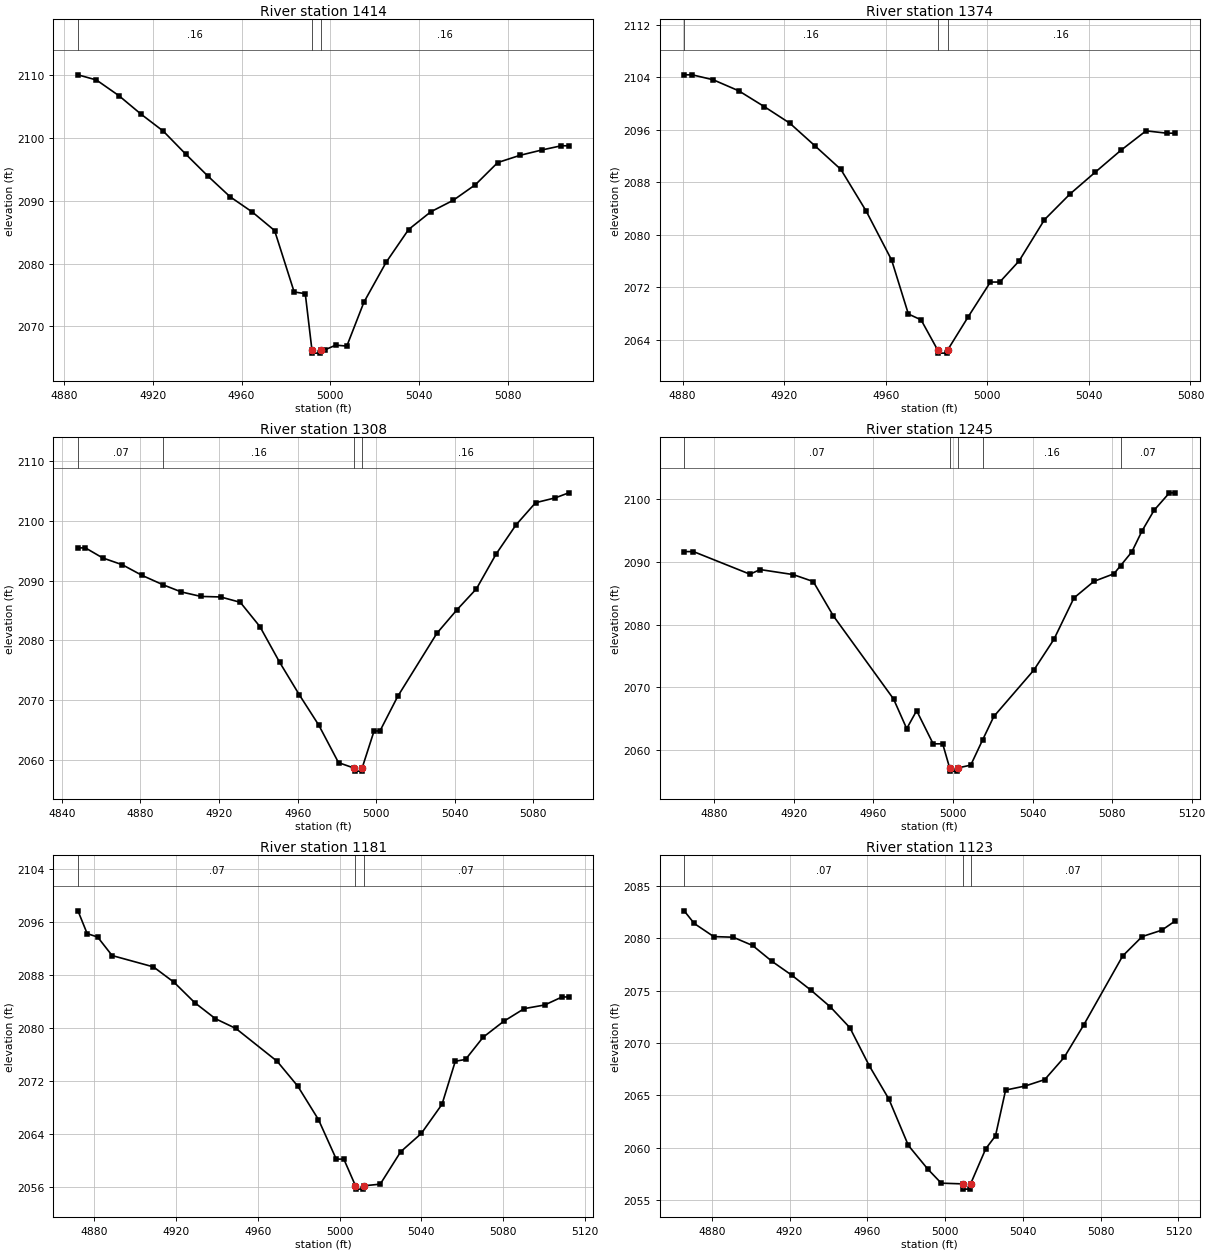
Type RM Length L Ch R = 1,1414,40,40,40
BEGIN DESCRIPTION:
Elm 83 1413.83
END DESCRIPTION:
XS GIS Cut Line= 3
      1534066.68      6767455.88      1534177.40      6767463.70
      1534286.81      6767453.28
#Sta/Elev= 30
  4886.4 2110.02  4894.7 2109.20  4904.8 2106.71  4914.8 2103.76  4924.8 2101.06
  4934.8 2097.44  4944.9 2093.90  4954.9 2090.61  4964.9 2088.18  4974.9 2085.24
  4983.7 2075.47  4988.7 2075.20  4991.7 2066.24  4991.9 2065.74  4995.4 2065.74
  4995.7 2066.24  4997.4 2066.24  5002.4 2067.01  5007.4 2066.86  5015.1 2073.85
  5025.1 2080.20  5035.2 2085.41  5045.2 2088.23  5055.3 2090.06  5065.3 2092.55
  5075.3 2096.06  5085.4 2097.22  5095.4 2098.08  5103.9 2098.73  5107.3 2098.73
#Mann=3,-1,0
  4886.4    0.16       0  4991.7    0.07       0  4995.7    0.16       0
Bank Sta=4991.7,4995.7
Exp/Cntr=0.3,0.1

Type RM Length L Ch R = 1,1374,66,66,66
BEGIN DESCRIPTION:
Elm 83 1373.92
END DESCRIPTION:
XS GIS Cut Line= 3
      1534083.62      6767484.53      1534207.35      6767496.25
      1534276.36      6767494.95
#Sta/Elev= 27
  4880.6 2104.40  4883.8 2104.40  4892.0 2103.65  4902.1 2101.96  4912.1 2099.56
  4922.2 2097.02  4932.2 2093.53  4942.3 2089.97  4952.3 2083.59  4962.3 2076.13
  4968.9 2067.89  4973.9 2067.00  4980.4 2062.42  4980.7 2061.92  4984.2 2061.92
  4984.4 2062.42  4992.5 2067.49  5001.2 2072.77  5004.9 2072.77  5012.5 2075.99
  5022.5 2082.29  5032.5 2086.19  5042.5 2089.54  5052.5 2092.85  5062.5 2095.85
  5070.7 2095.49  5073.9 2095.49
#Mann=3,-1,0
  4880.6    0.16       0  4980.4    0.07       0  4984.4    0.16       0
Bank Sta=4980.4,4984.4
Exp/Cntr=0.3,0.1

Type RM Length L Ch R = 1,1308,63,63,63
BEGIN DESCRIPTION:
Elm 83 1308.17
END DESCRIPTION:
XS GIS Cut Line= 3
      1534052.40      6767557.45      1534206.05      6767561.36
      1534301.84      6767553.69
#Sta/Elev= 30
  4848.2 2095.46  4852.0 2095.46  4860.8 2093.78  4870.8 2092.64  4880.8 2090.87
  4891.4 2089.31  4900.8 2088.10  4910.8 2087.35  4920.8 2087.26  4930.8 2086.37
  4940.8 2082.31  4950.8 2076.37  4960.8 2070.94  4970.8 2065.82  4980.8 2059.58
  4988.8 2058.66  4989.1 2058.16  4992.6 2058.16  4992.8 2058.66  4998.9 2064.87
  5001.9 2064.87  5010.9 2070.63  5030.9 2081.21  5041.0 2085.09  5051.0 2088.63
  5061.0 2094.43  5071.1 2099.29  5081.1 2103.01  5091.1 2103.82  5098.0 2104.66
#Mann=4,-1,0
  4848.2    0.07       0  4891.4    0.16       0  4988.8    0.07       0
  4992.8    0.16       0
Bank Sta=4988.8,4992.8
Exp/Cntr=0.3,0.1

Type RM Length L Ch R = 1,1245,64,64,64
BEGIN DESCRIPTION:
Elm 83 1244.95
END DESCRIPTION:
XS GIS Cut Line= 3
      1534070.63      6767608.23      1534199.54      6767625.16
      1534315.45      6767610.83
#Sta/Elev= 30
  4864.8 2091.67  4869.5 2091.67  4897.9 2088.06  4903.0 2088.80  4919.6 2088.00
  4929.7 2086.89  4939.8 2081.41  4970.1 2068.12  4976.7 2063.39  4981.7 2066.26
  4990.0 2060.96  4994.8 2060.96  4998.3 2057.10  4998.6 2056.60  5002.1 2056.60
  5002.3 2057.10  5008.9 2057.56  5014.9 2061.61  5020.5 2065.33  5040.6 2072.73
  5050.7 2077.64  5060.8 2084.27  5070.8 2086.91  5080.9 2088.13  5084.3 2089.45
  5089.9 2091.63  5095.0 2094.96  5101.1 2098.28  5108.8 2101.06  5111.6 2101.06
#Mann=5,-1,0
  4864.8    0.07       0  4998.3    0.07       0  5002.3    0.07       0
  5014.9    0.16       0  5084.3    0.07       0
Bank Sta=4998.3,5002.3
Exp/Cntr=0.3,0.1

Type RM Length L Ch R = 1,1181,58,58,58
BEGIN DESCRIPTION:
Elm 83 1180.79
END DESCRIPTION:
XS GIS Cut Line= 3
      1534078.42      6767672.03      1534207.35      6767688.96
      1534316.69      6767677.25
#Sta/Elev= 30
  4872.1 2097.75  4876.6 2094.31  4881.7 2093.80  4888.8 2091.00  4909.0 2089.29
  4919.1 2086.96  4929.2 2083.89  4939.3 2081.47  4949.3 2080.00  4969.5 2075.04
  4979.6 2071.28  4989.7 2066.24  4998.4 2060.28  5002.1 2060.28  5007.8 2056.25
  5008.1 2055.75  5011.6 2055.75  5011.8 2056.25  5019.9 2056.50  5029.9 2061.39
  5040.0 2064.16  5050.1 2068.55  5056.6 2075.05  5061.6 2075.32  5070.2 2078.67
  5080.2 2081.06  5090.3 2082.99  5100.3 2083.54  5108.8 2084.75  5112.1 2084.75
#Mann=3,-1,0
  4872.1    0.07       0  5007.8    0.07       0  5011.8    0.07       0
Bank Sta=5007.8,5011.8
Exp/Cntr=0.3,0.1

Type RM Length L Ch R = 1,1123,74,74,74
BEGIN DESCRIPTION:
Elm 83 1122.9
END DESCRIPTION:
XS GIS Cut Line= 3
      1534079.77      6767747.55      1534213.86      6767744.95
      1534331.80      6767735.98
#Sta/Elev= 30
  4865.8 2082.61  4871.0 2081.40  4881.0 2080.15  4891.0 2080.09  4901.0 2079.30
  4911.0 2077.78  4921.0 2076.48  4931.0 2075.03  4941.0 2073.43  4951.0 2071.45
  4961.0 2067.81  4971.1 2064.62  4981.1 2060.20  4991.1 2057.94  4998.0 2056.60
  5009.1 2056.53  5009.3 2056.03  5012.8 2056.03  5013.1 2056.53  5020.9 2059.89
  5025.9 2061.12  5031.1 2065.49  5041.2 2065.88  5051.2 2066.49  5061.2 2068.61
  5071.3 2071.72  5091.3 2078.30  5101.3 2080.15  5111.4 2080.76  5118.2 2081.63
#Mann=3,-1,0
  4865.8    0.07       0  5009.1    0.07       0  5013.1    0.07       0
Bank Sta=5009.1,5013.1
Exp/Cntr=0.3,0.1

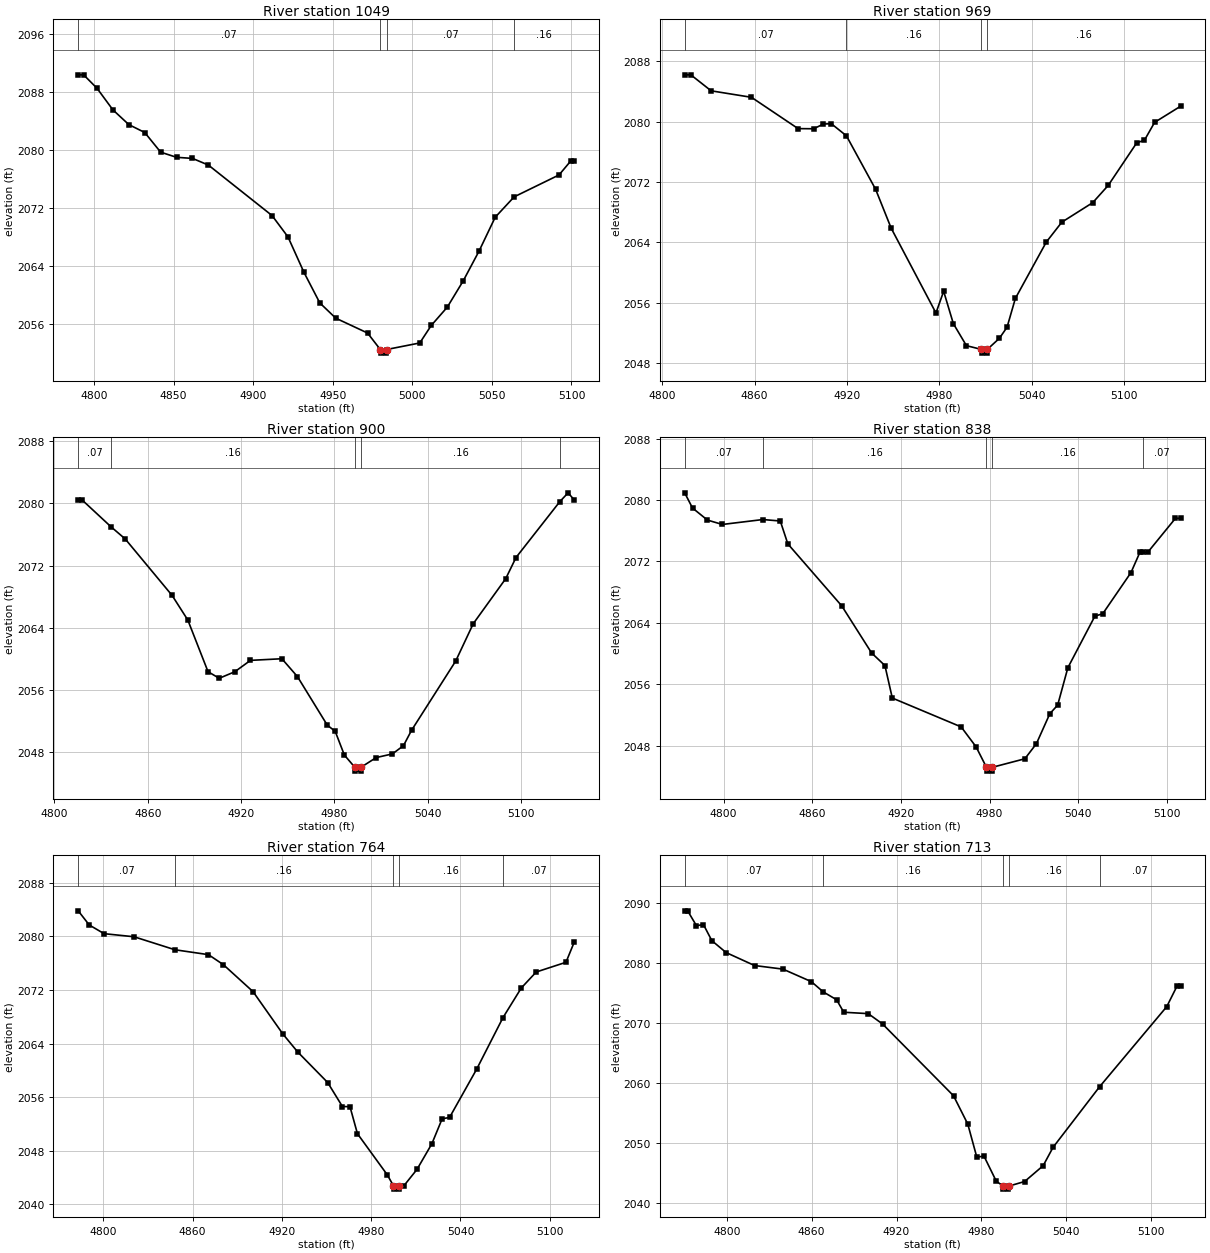
Type RM Length L Ch R = 1,1049,80,80,80
BEGIN DESCRIPTION:
Elm 83 1049.09
END DESCRIPTION:
XS GIS Cut Line= 3
      1534043.25      6767810.05      1534255.53      6767804.85
      1534354.48      6767812.66
#Sta/Elev= 30
  4790.1 2090.32  4793.5 2090.32  4801.9 2088.47  4811.9 2085.49  4821.9 2083.46
  4831.9 2082.37  4841.9 2079.66  4851.9 2078.95  4861.9 2078.80  4871.9 2077.88
  4911.9 2070.92  4921.9 2067.98  4931.9 2063.11  4941.9 2058.88  4951.9 2056.78
  4971.9 2054.73  4979.9 2052.46  4980.2 2051.96  4983.7 2051.96  4983.9 2052.46
  5004.7 2053.36  5011.9 2055.77  5022.0 2058.30  5032.0 2061.92  5042.0 2066.05
  5052.1 2070.69  5064.0 2073.50  5092.2 2076.52  5099.5 2078.43  5101.7 2078.43
#Mann=4,-1,0
  4790.1    0.07       0  4979.9    0.07       0  4983.9    0.07       0
  5064.0    0.16       0
Bank Sta=4979.9,4983.9
Exp/Cntr=0.3,0.1

Type RM Length L Ch R = 1,969,69,69,69
BEGIN DESCRIPTION:
Elm 83 968.53
END DESCRIPTION:
XS GIS Cut Line= 3
      1534071.98      6767860.84      1534256.83      6767885.57
      1534391.75      6767870.16
#Sta/Elev= 30
  4814.6 2086.21  4818.6 2086.21  4831.8 2084.09  4858.0 2083.23  4888.3 2079.08
  4898.4 2079.06  4904.8 2079.69  4909.9 2079.73  4919.7 2078.13  4938.7 2071.03
  4948.8 2065.88  4977.9 2054.64  4982.9 2057.52  4989.2 2053.23  4997.7 2050.31
  5007.3 2049.82  5007.6 2049.32  5011.1 2049.32  5011.3 2049.82  5019.1 2051.28
  5024.1 2052.75  5029.5 2056.57  5049.6 2064.04  5059.7 2066.68  5079.8 2069.27
  5089.8 2071.54  5108.4 2077.20  5113.4 2077.54  5120.0 2079.91  5136.9 2082.05
#Mann=4,-1,0
  4814.6    0.07       0  4919.7    0.16       0  5007.3    0.07       0
  5011.3    0.16       0
Bank Sta=5007.3,5011.3
Exp/Cntr=0.3,0.1

Type RM Length L Ch R = 1,900,62,62,62
BEGIN DESCRIPTION:
Elm 83 900.41
END DESCRIPTION:
XS GIS Cut Line= 3
      1534085.00      6767972.81      1534267.25      6767950.68
      1534397.30      6767912.96
#Sta/Elev= 30
  4815.3 2080.45  4817.8 2080.45  4836.4 2076.99  4845.5 2075.43  4875.7 2068.14
  4885.8 2064.97  4898.8 2058.31  4906.0 2057.46  4916.0 2058.30  4926.1 2059.77
  4946.3 2059.98  4956.3 2057.68  4975.5 2051.42  4980.6 2050.62  4986.5 2047.56
  4993.2 2045.99  4993.5 2045.49  4997.0 2045.49  4997.2 2045.99  5007.0 2047.24
  5017.4 2047.71  5024.5 2048.77  5029.7 2050.75  5058.1 2059.68  5069.4 2064.50
  5090.3 2070.31  5096.9 2073.03  5125.1 2080.24  5130.4 2081.37  5134.3 2080.47
#Mann=5,-1,0
  4815.3    0.07       0  4836.4    0.16       0  4993.2    0.07       0
  4997.2    0.16       0  5125.1    0.07       0
Bank Sta=4993.2,4997.2
Exp/Cntr=0.3,0.1

Type RM Length L Ch R = 1,838,74,74,74
BEGIN DESCRIPTION:
Elm 83 837.7
END DESCRIPTION:
XS GIS Cut Line= 3
      1534079.77      6768032.71      1534307.61      6768000.16
      1534406.55      6767963.71
#Sta/Elev= 30
  4773.7 2080.94  4779.0 2078.96  4789.1 2077.39  4799.2 2076.82  4826.6 2077.46
  4838.4 2077.27  4843.5 2074.29  4880.0 2066.21  4900.2 2060.08  4909.2 2058.44
  4914.2 2054.21  4960.8 2050.45  4970.9 2047.85  4977.9 2045.19  4978.1 2044.69
  4981.6 2044.69  4981.9 2045.19  5003.9 2046.30  5011.7 2048.26  5020.8 2052.17
  5026.1 2053.29  5033.0 2058.16  5051.3 2064.88  5056.6 2065.19  5075.7 2070.55
  5081.7 2073.17  5083.9 2073.17  5087.0 2073.18  5105.8 2077.62  5109.3 2077.62
#Mann=5,-1,0
  4773.7    0.07       0  4826.6    0.16       0  4977.9    0.07       0
  4981.9    0.16       0  5083.9    0.07       0
Bank Sta=4977.9,4981.9
Exp/Cntr=0.3,0.1

Type RM Length L Ch R = 1,764,51,51,51
BEGIN DESCRIPTION:
Elm 83 764.1
END DESCRIPTION:
XS GIS Cut Line= 3
      1534087.58      6768065.26      1534302.40      6768074.38
      1534420.48      6768069.19
#Sta/Elev= 30
  4783.2 2083.81  4790.6 2081.70  4800.6 2080.40  4820.7 2079.94  4848.2 2078.00
  4870.7 2077.27  4880.7 2075.78  4900.7 2071.74  4920.7 2065.43  4930.7 2062.74
  4950.8 2058.19  4960.7 2054.61  4965.8 2054.58  4970.8 2050.55  4990.8 2044.43
  4995.0 2042.78  4995.3 2042.28  4998.8 2042.28  4999.0 2042.78  5002.0 2042.78
  5010.8 2045.22  5020.8 2049.05  5027.7 2052.77  5032.7 2052.98  5050.9 2060.18
  5068.6 2067.88  5080.9 2072.30  5090.9 2074.68  5110.9 2076.13  5116.4 2079.11
#Mann=5,-1,0
  4783.2    0.07       0  4848.2    0.16       0  4995.0    0.07       0
  4999.0    0.16       0  5068.6    0.07       0
Bank Sta=4995,4999
Exp/Cntr=0.3,0.1

Type RM Length L Ch R = 1,713,62,62,62
BEGIN DESCRIPTION:
Elm 83 713.31
END DESCRIPTION:
XS GIS Cut Line= 3
      1534075.87      6768101.72      1534303.70      6768125.16
      1534424.80      6768113.44
#Sta/Elev= 30
  4770.2 2088.67  4772.3 2088.67  4778.5 2086.20  4783.5 2086.37  4789.4 2083.70
  4799.5 2081.71  4819.6 2079.55  4839.7 2078.95  4859.8 2076.86  4868.2 2075.15
  4877.6 2073.85  4882.7 2071.76  4900.0 2071.53  4910.1 2069.81  4960.3 2057.84
  4970.4 2053.11  4976.8 2047.58  4981.8 2047.80  4990.5 2043.61  4995.4 2042.77
  4995.6 2042.27  4999.1 2042.27  4999.4 2042.77  5010.6 2043.54  5023.7 2046.18
  5030.7 2049.24  5063.7 2059.37  5111.1 2072.70  5118.5 2076.19  5120.9 2076.19
#Mann=5,-1,0
  4770.2    0.07       0  4868.2    0.16       0  4995.4    0.07       0
  4999.4    0.16       0  5063.7    0.07       0
Bank Sta=4995.4,4999.4
Exp/Cntr=0.3,0.1

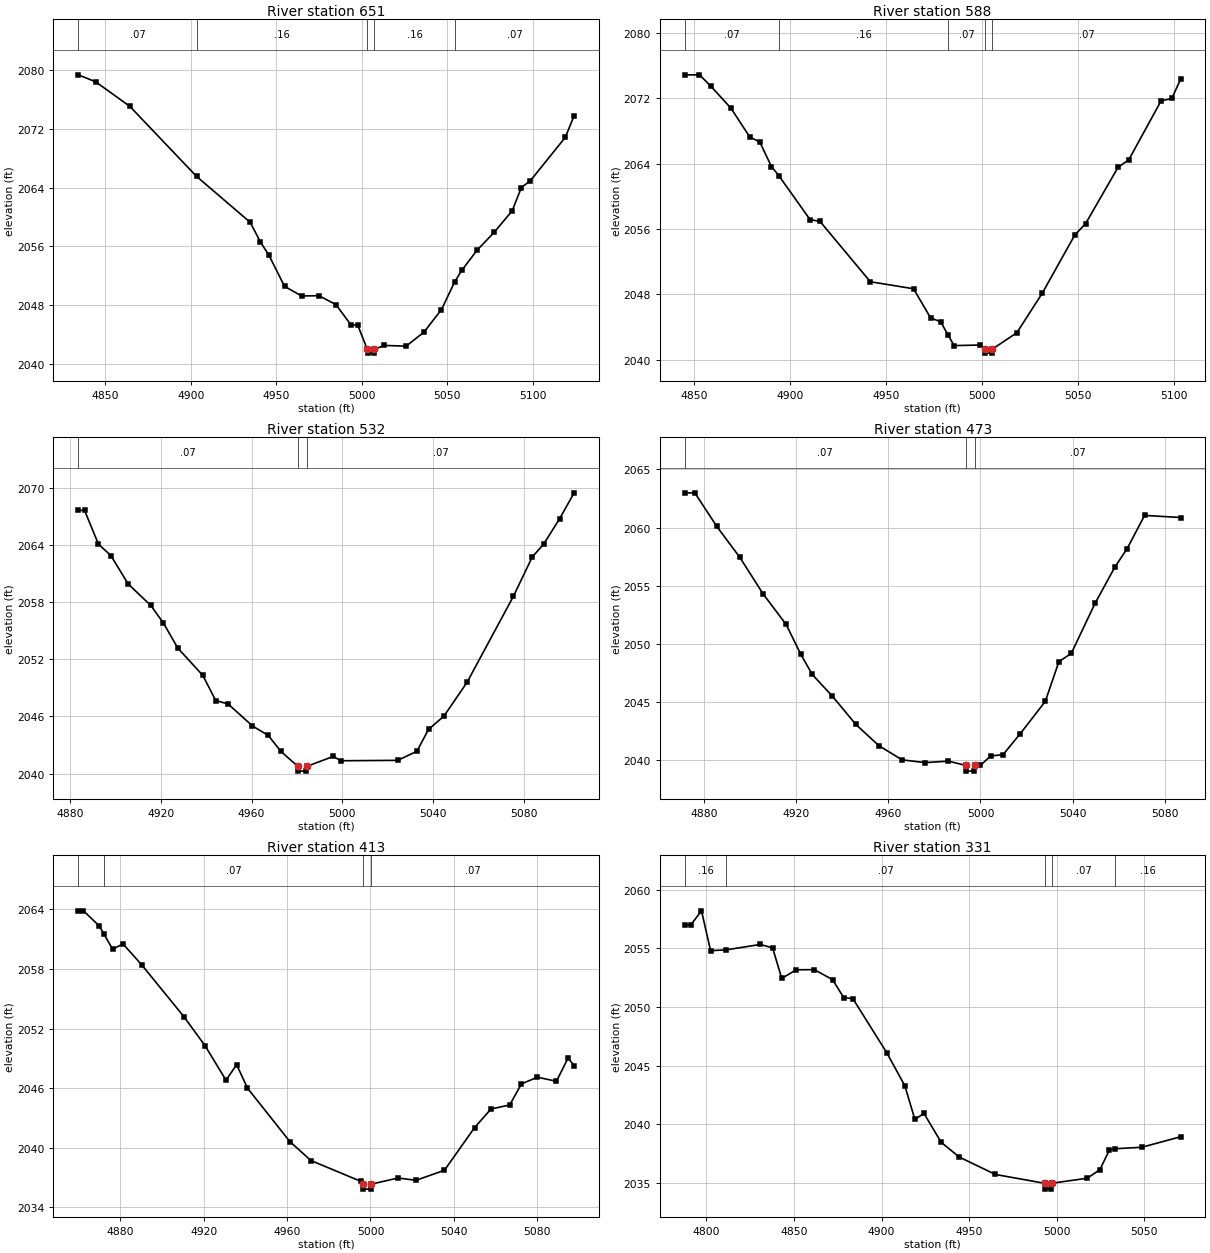
Type RM Length L Ch R = 1,651,63,63,63
BEGIN DESCRIPTION:
Elm 83 650.53
END DESCRIPTION:
XS GIS Cut Line= 3
      1534144.89      6768203.28      1534307.61      6768187.66
      1534429.99      6768155.11
#Sta/Elev= 30
  4834.1 2079.40  4844.3 2078.45  4864.3 2075.10  4903.3 2065.56  4934.7 2059.29
  4940.7 2056.61  4945.7 2054.79  4954.8 2050.56  4964.8 2049.25  4974.9 2049.29
  4984.9 2048.07  4993.7 2045.29  4997.6 2045.29  5003.2 2041.96  5003.5 2041.46
  5007.0 2041.46  5007.2 2041.96  5013.0 2042.51  5025.9 2042.41  5036.3 2044.31
  5046.6 2047.40  5054.3 2051.17  5058.4 2052.73  5067.3 2055.46  5077.6 2057.98
  5088.0 2060.88  5093.3 2064.03  5098.5 2064.94  5119.0 2070.87  5124.2 2073.83
#Mann=5,-1,0
  4834.1    0.07       0  4903.3    0.16       0  5003.2    0.07       0
  5007.2    0.16       0  5054.3    0.07       0
Bank Sta=5003.2,5007.2
Exp/Cntr=0.3,0.1

Type RM Length L Ch R = 1,588,56,56,56
BEGIN DESCRIPTION:
Elm 83 588.3
END DESCRIPTION:
XS GIS Cut Line= 3
      1534202.16      6768285.31      1534347.98      6768235.84
      1534441.53      6768189.70
#Sta/Elev= 30
  4845.3 2074.84  4853.0 2074.85  4858.9 2073.47  4869.4 2070.77  4879.2 2067.25
  4884.4 2066.64  4890.5 2063.63  4894.3 2062.53  4910.6 2057.15  4915.8 2056.92
  4942.0 2049.55  4964.5 2048.69  4973.4 2045.12  4978.6 2044.66  4982.6 2042.99
  4985.6 2041.74  4999.3 2041.81  5001.6 2041.32  5001.9 2040.82  5005.4 2040.82
  5005.6 2041.32  5018.3 2043.31  5031.6 2048.17  5048.5 2055.27  5054.1 2056.65
  5071.0 2063.54  5076.6 2064.46  5093.4 2071.66  5099.0 2071.96  5103.6 2074.32
#Mann=5,-1,0
  4845.3    0.07       0  4894.3    0.16       0  4982.6    0.07       0
  5001.6    0.07       0  5005.6    0.07       0
Bank Sta=5001.6,5005.6
Exp/Cntr=0.3,0.1

Type RM Length L Ch R = 1,532,59,59,59
BEGIN DESCRIPTION:
Elm 83 532.168
END DESCRIPTION:
XS GIS Cut Line= 3
      1534254.96      6768338.02      1534361.08      6768290.20
      1534461.25      6768269.95
#Sta/Elev= 30
  4883.6 2067.61  4886.4 2067.61  4892.5 2064.07  4898.0 2062.87  4905.6 2059.89
  4915.6 2057.63  4921.1 2055.81  4927.5 2053.16  4938.5 2050.30  4944.2 2047.66
  4949.7 2047.29  4960.4 2044.99  4967.4 2043.99  4972.9 2042.33  4980.4 2040.75
  4980.6 2040.25  4984.1 2040.25  4984.4 2040.75  4996.0 2041.79  4999.4 2041.34
  5024.4 2041.38  5032.9 2042.33  5038.0 2044.63  5044.8 2046.02  5055.0 2049.57
  5075.4 2058.58  5083.7 2062.71  5088.8 2064.08  5095.8 2066.74  5102.2 2069.45
#Mann=3,-1,0
  4883.6    0.07       0  4980.4    0.07       0  4984.4    0.07       0
Bank Sta=4980.4,4984.4
Exp/Cntr=0.3,0.1

Type RM Length L Ch R = 1,473,60,60,60
BEGIN DESCRIPTION:
Elm 83 4131
END DESCRIPTION:
XS GIS Cut Line= 3
      1534271.16      6768347.81      1534398.90      6768335.81
      1534479.48      6768303.55
#Sta/Elev= 30
  4871.7 2062.98  4876.1 2062.98  4885.6 2060.10  4895.6 2057.44  4905.7 2054.30
  4915.7 2051.67  4922.0 2049.13  4927.0 2047.38  4935.8 2045.50  4945.9 2043.09
  4955.9 2041.26  4966.0 2040.04  4976.0 2039.80  4986.0 2039.93  4993.5 2039.57
  4993.8 2039.07  4997.3 2039.07  4997.5 2039.57  5000.0 2039.57  5004.4 2040.37
  5009.8 2040.49  5017.3 2042.30  5028.1 2045.06  5034.0 2048.47  5039.4 2049.19
  5049.7 2053.49  5058.2 2056.57  5063.6 2058.19  5071.2 2061.04  5086.8 2060.86
#Mann=3,-1,0
  4871.7    0.07       0  4993.5    0.07       0  4997.5    0.07       0
Bank Sta=4993.5,4997.5
Exp/Cntr=0.3,0.1

Type RM Length L Ch R = 1,413,82,82,82
BEGIN DESCRIPTION:
Elm 83 4130
END DESCRIPTION:
XS GIS Cut Line= 3
      1534275.05      6768369.95      1534413.16      6768394.05
      1534500.78      6768350.83
#Sta/Elev= 30
  4859.8 2063.84  4862.3 2063.84  4869.9 2062.32  4872.2 2061.48  4876.3 2059.98
  4881.3 2060.51  4890.2 2058.42  4910.5 2053.19  4920.7 2050.25  4930.7 2046.80
  4935.8 2048.36  4941.0 2046.00  4961.3 2040.63  4971.4 2038.72  4995.3 2036.63
  4996.4 2036.34  4996.6 2035.84  5000.1 2035.84  5000.4 2036.34  5013.2 2036.96
  5021.9 2036.73  5035.5 2037.74  5049.9 2042.02  5057.8 2043.90  5066.8 2044.31
  5072.4 2046.43  5080.1 2047.10  5089.2 2046.69  5094.8 2049.04  5097.7 2048.25
#Mann=4,-1,0
  4859.8    0.16       0  4872.2    0.07       0  4996.4    0.07       0
  5000.4    0.07       0
Bank Sta=4996.4,5000.4
Exp/Cntr=0.3,0.1

Type RM Length L Ch R = 1,331,63,63,63
BEGIN DESCRIPTION:
Elm 83 4129
END DESCRIPTION:
XS GIS Cut Line= 3
      1534263.32      6768399.89      1534468.93      6768453.19
      1534534.16      6768425.94
#Sta/Elev= 30
  4787.6 2057.00  4791.1 2057.00  4797.2 2058.20  4802.4 2054.80  4811.4 2054.87
  4830.7 2055.33  4837.8 2055.04  4843.0 2052.43  4851.3 2053.17  4861.6 2053.18
  4872.0 2052.33  4878.4 2050.79  4883.6 2050.71  4903.0 2046.08  4913.3 2043.26
  4919.0 2040.40  4924.2 2040.91  4934.0 2038.45  4944.3 2037.19  4965.0 2035.70
  4993.0 2034.95  4993.3 2034.45  4996.8 2034.45  4997.0 2034.95  5017.4 2035.38
  5024.6 2036.11  5030.1 2037.80  5033.5 2037.90  5048.5 2038.02  5070.7 2038.92
#Mann=5,-1,0
  4787.6    0.16       0  4811.4    0.07       0  4993.0    0.07       0
  4997.0    0.07       0  5033.5    0.16       0
Bank Sta=4993,4997
Exp/Cntr=0.3,0.1

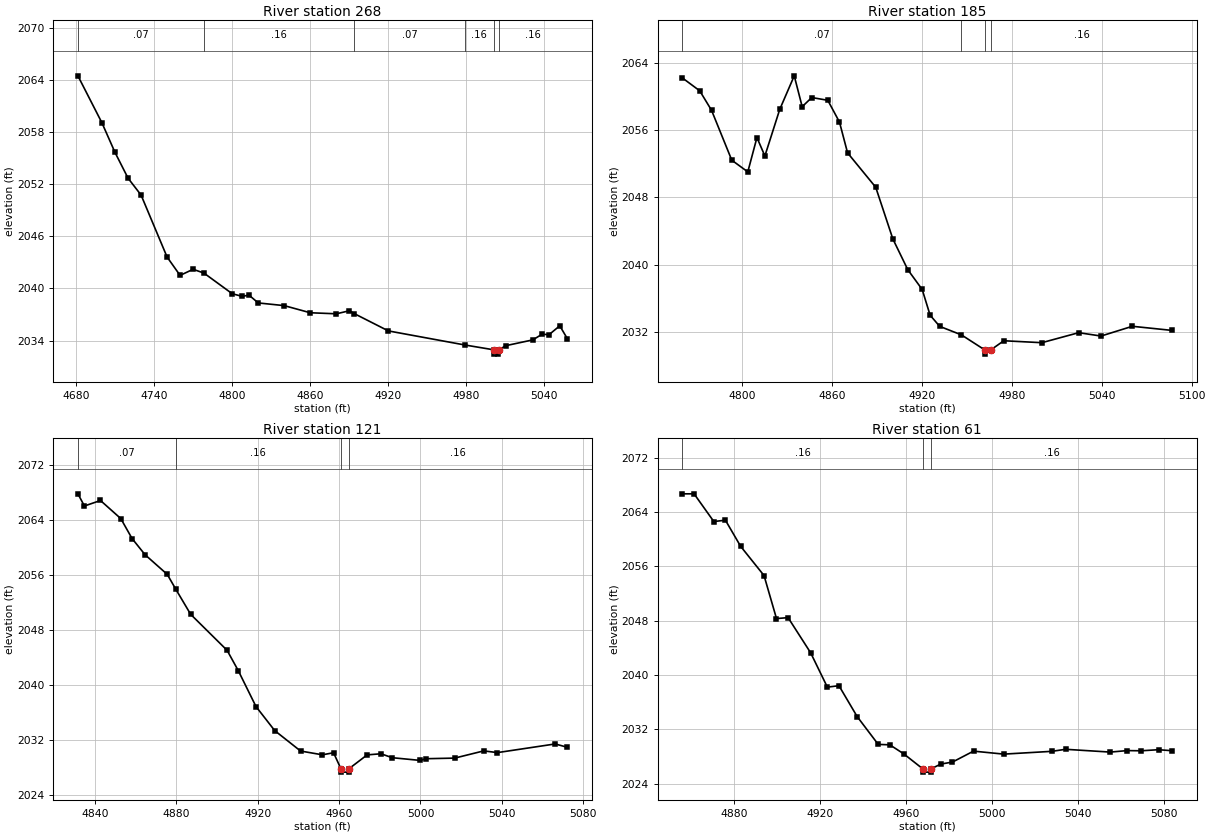
Type RM Length L Ch R = 1,268,83,83,83
BEGIN DESCRIPTION:
Elm 83 4128
END DESCRIPTION:
XS GIS Cut Line= 3
      1534186.50      6768519.69      1534504.47      6768503.22
      1534560.72      6768488.65
#Sta/Elev= 30
  4681.6 2064.46  4700.1 2059.05  4710.1 2055.66  4720.2 2052.68  4730.2 2050.74
  4750.2 2043.61  4760.2 2041.50  4770.2 2042.20  4778.5 2041.77  4800.3 2039.39
  4808.1 2039.08  4813.1 2039.24  4820.3 2038.33  4840.3 2038.02  4860.3 2037.20
  4880.4 2037.08  4890.4 2037.43  4894.3 2037.09  4920.4 2035.11  4979.3 2033.49
  5001.3 2032.94  5001.5 2032.44  5005.0 2032.44  5005.3 2032.94  5010.9 2033.42
  5031.5 2034.08  5038.7 2034.74  5043.9 2034.67  5052.2 2035.70  5058.1 2034.20
#Mann=6,-1,0
  4681.6    0.07       0  4778.5    0.16       0  4894.3    0.07       0
  4979.3    0.16       0  5001.3    0.07       0  5005.3    0.16       0
Bank Sta=5001.3,5005.3
Exp/Cntr=0.3,0.1

Type RM Length L Ch R = 1,185,64,64,64
BEGIN DESCRIPTION:
Elm 83 4127
END DESCRIPTION:
XS GIS Cut Line= 3
      1534284.22      6768670.71      1534508.82      6768586.42
      1534580.02      6768536.60
#Sta/Elev= 30
  4760.1 2062.20  4771.6 2060.68  4779.5 2058.36  4793.0 2052.43  4803.7 2051.04
  4809.8 2055.12  4815.1 2052.93  4825.0 2058.46  4834.7 2062.46  4840.0 2058.79
  4846.4 2059.88  4857.1 2059.55  4864.9 2056.96  4870.3 2053.30  4889.1 2049.21
  4900.5 2043.08  4910.5 2039.41  4920.1 2037.06  4925.4 2034.00  4931.8 2032.67
  4946.3 2031.66  4961.9 2029.87  4962.1 2029.37  4965.9 2029.87  4974.6 2030.96
  5000.0 2030.73  5024.6 2031.92  5039.5 2031.52  5060.4 2032.68  5086.9 2032.19
#Mann=4,-1,0
  4760.1    0.07       0  4946.3    0.16       0  4961.9    0.07       0
  4965.9    0.16       0
Bank Sta=4961.9,4965.9
Exp/Cntr=0.3,0.1

Type RM Length L Ch R = 1,121,60,60,60
BEGIN DESCRIPTION:
Elm 83 4126
END DESCRIPTION:
XS GIS Cut Line= 3
      1534394.81      6768703.30      1534548.97      6768635.78
      1534597.05      6768581.92
#Sta/Elev= 30
  4831.7 2067.78  4834.9 2066.01  4842.8 2066.81  4852.8 2064.17  4858.3 2061.28
  4864.7 2058.92  4875.6 2056.06  4879.8 2053.90  4887.1 2050.25  4905.0 2045.01
  4910.5 2042.05  4919.2 2036.83  4928.4 2033.33  4941.1 2030.36  4951.8 2029.81
  4957.3 2030.11  4960.9 2027.79  4961.2 2027.29  4964.7 2027.29  4964.9 2027.79
  4973.8 2029.80  4980.6 2029.96  4986.1 2029.39  5000.0 2028.99  5002.6 2029.24
  5016.8 2029.33  5031.1 2030.38  5037.8 2030.13  5066.2 2031.39  5072.2 2030.90
#Mann=4,-1,0
  4831.7    0.07       0  4879.8    0.16       0  4960.9    0.07       0
  4964.9    0.16       0
Bank Sta=4960.9,4964.9
Exp/Cntr=0.3,0.1

Type RM Length L Ch R = 1,61,0,0,0
BEGIN DESCRIPTION:
Elm 83 4125
END DESCRIPTION:
XS GIS Cut Line= 3
      1534430.03      6768750.15      1534562.91      6768694.15
      1534628.57      6768641.92
#Sta/Elev= 30
  4855.8 2066.66  4861.2 2066.66  4870.4 2062.58  4875.8 2062.78  4882.9 2058.93
  4893.8 2054.63  4899.6 2048.30  4905.0 2048.44  4915.5 2043.27  4923.3 2038.21
  4928.7 2038.42  4937.2 2033.87  4947.0 2029.78  4952.4 2029.72  4958.9 2028.39
  4967.7 2026.20  4968.0 2025.70  4971.5 2025.70  4971.7 2026.20  4976.2 2026.89
  4981.6 2027.18  4991.4 2028.79  5005.5 2028.35  5027.9 2028.76  5034.3 2029.06
  5055.1 2028.65  5063.1 2028.87  5069.5 2028.84  5077.6 2029.00  5083.9 2028.85
#Mann=3,-1,0
  4855.8    0.16       0  4967.7    0.07       0  4971.7    0.16       0
Bank Sta=4967.7,4971.7
Exp/Cntr=0.3,0.1

Chan Stop Cuts=-1