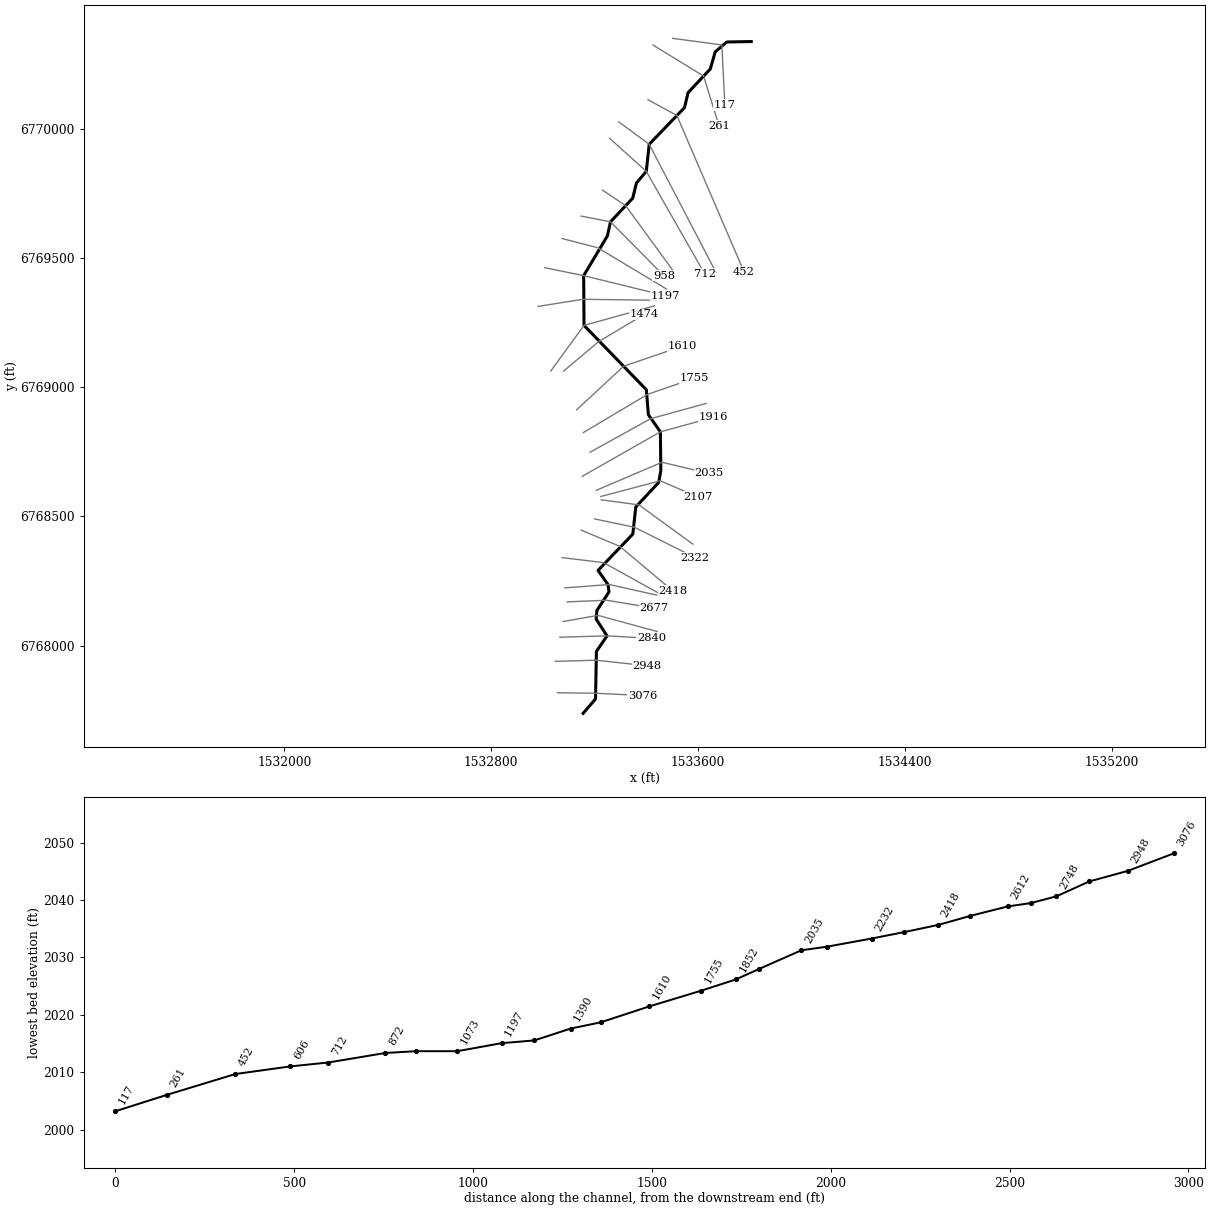
--- Elm 84.prj (project) ---

Proj Title=Elm 84 Base Level Engineering
Current Plan=p01
Default Exp/Contr=0.3,0.1
English Units
Geom File=g01
Flow File=f01
Plan File=p01
BEGIN DESCRIPTION:
Elm 84
END DESCRIPTION:

--- Elm 84.p01 (plan) ---

Plan Title=Multiple Run
Short Identifier=Multiple
Geom File=g01
Flow File=f01
Subcritical Flow
K Sum by GR= 0
Std Step Tol= 0.01
Critical Tol= 0.01
Num of Std Step Trials= 20
Max Error Tol= 0.3
Flow Tol Ratio= 0.001
Split Flow NTrial= 30
Split Flow Tol= 0.02
Split Flow Ratio= 0.02
Log Output Level= 0
Friction Slope Method= 1
Unsteady Friction Slope Method= 2
Unsteady Bridges Friction Slope Method= 1
Parabolic Critical Depth
Global Vel Dist=  1 , 1 , 1
Global Log Level= 0
CheckData=True
Encroach Param= -1, 0, 0, 0
BEGIN DESCRIPTION:
Multiple Run
END DESCRIPTION:

--- Elm 84.f01 (steady flow) ---

Flow Title=Multiple
Number of Profiles=7
Profile Names=10-year,25-year,50-year,1pct_min,100-year,1pct_plu,500-year
River Rch & RM= Elm 84,Reach-1,3076
      75      96     113      83     133     183     185
Boundary for River Rch & Prof#=Elm 84,Reach-1,1
Up Type=0
Dn Type=3
Dn Slope=0.005
Boundary for River Rch & Prof#=Elm 84,Reach-1,2
Up Type=0
Dn Type=3
Dn Slope=0.005
Boundary for River Rch & Prof#=Elm 84,Reach-1,3
Up Type=0
Dn Type=3
Dn Slope=0.005
Boundary for River Rch & Prof#=Elm 84,Reach-1,4
Up Type=0
Dn Type=3
Dn Slope=0.005
Boundary for River Rch & Prof#=Elm 84,Reach-1,5
Up Type=0
Dn Type=3
Dn Slope=0.005
Boundary for River Rch & Prof#=Elm 84,Reach-1,6
Up Type=0
Dn Type=3
Dn Slope=0.005
Boundary for River Rch & Prof#=Elm 84,Reach-1,7
Up Type=0
Dn Type=3
Dn Slope=0.005

--- Elm 84.g01 (geometry) ---

Geom Title=Existing Conditions

River Reach=Elm 84,Reach-1
Reach XY= 30
      1533155.00      6767738.00      1533203.11      6767793.78
      1533206.38      6767977.56      1533247.41      6768038.01
      1533205.23      6768103.34      1533208.43      6768136.27
      1533255.19      6768208.20      1533251.38      6768236.37
      1533212.82      6768291.41      1533347.14      6768431.83
      1533358.63      6768536.50      1533447.17      6768631.82
      1533455.50      6768677.80      1533453.78      6768827.50
      1533407.36      6768893.98      1533399.48      6768990.43
      1533158.53      6769239.46      1533157.24      6769432.07
      1533248.90      6769585.81      1533260.85      6769640.29
      1533346.84      6769731.95      1533361.14      6769790.17
      1533399.23      6769835.68      1533410.52      6769940.43
      1533546.84      6770081.95      1533560.87      6770140.28
      1533646.82      6770231.98      1533665.61      6770298.05
      1533710.55      6770336.23      1533805.00      6770338.00

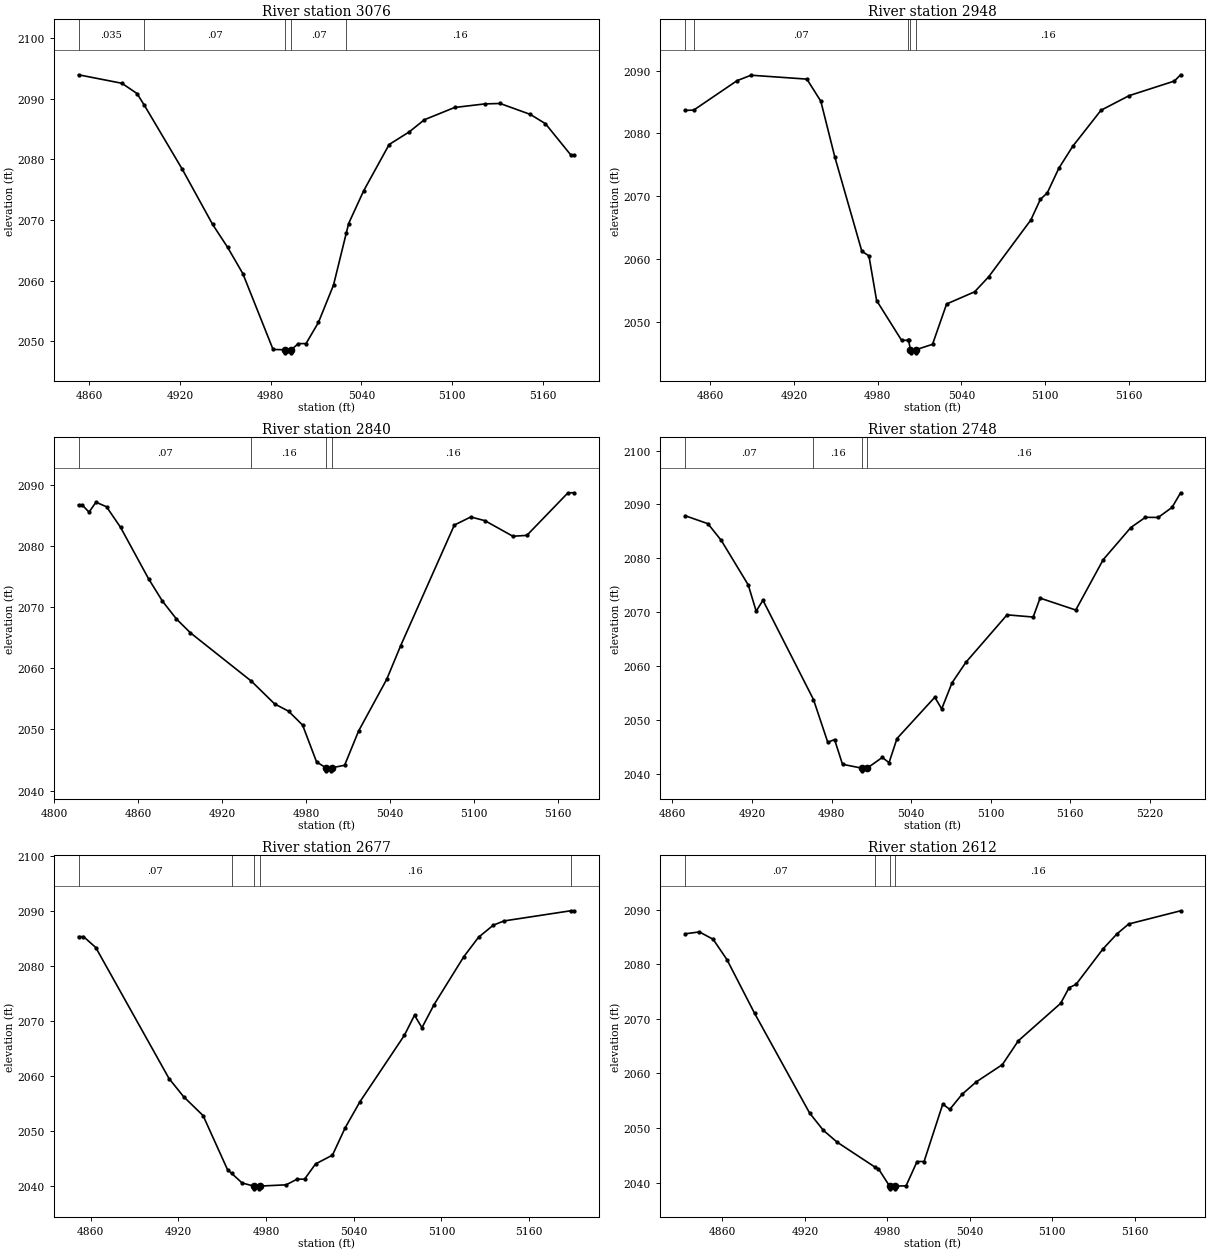
Type RM Length L Ch R = 1,3076,128,128,128
BEGIN DESCRIPTION:
Elm 84 4234
END DESCRIPTION:
XS GIS Cut Line= 3
      1533056.31      6767817.87      1533203.50      6767815.97
      1533383.98      6767807.02
#Sta/Elev= 30
  4852.8 2093.93  4881.5 2092.53  4891.5 2090.84  4896.4 2088.89  4921.5 2078.34
  4941.5 2069.28  4951.5 2065.47  4961.5 2061.17  4981.5 2048.67  4989.5 2048.61
  4989.7 2048.11  4993.2 2048.11  4993.5 2048.61  4998.2 2049.63  5003.3 2049.63
  5011.5 2053.11  5021.5 2059.28  5030.0 2067.90  5031.5 2069.42  5041.5 2074.84
  5058.3 2082.44  5071.6 2084.52  5081.6 2086.52  5101.6 2088.54  5121.6 2089.13
  5131.7 2089.20  5151.7 2087.40  5161.7 2085.87  5178.7 2080.65  5180.7 2080.65
#Mann=5,-1,0
  4852.8   0.035       0  4896.4    0.07       0  4989.5    0.07       0
  4993.5    0.07       0  5030.0    0.16       0
Bank Sta=4989.5,4993.5
Exp/Cntr=0.3,0.1

Type RM Length L Ch R = 1,2948,108,108,108
BEGIN DESCRIPTION:
Elm 84 4233
END DESCRIPTION:
XS GIS Cut Line= 3
      1533047.64      6767939.39      1533205.78      6767943.74
      1533401.80      6767922.22
#Sta/Elev= 30
  4841.8 2083.67  4848.1 2083.73  4879.2 2088.42  4889.2 2089.28  4929.2 2088.66
  4939.2 2085.14  4949.2 2076.29  4968.6 2061.26  4973.7 2060.51  4979.2 2053.40
  4997.1 2047.07  5001.5 2047.07  5002.1 2047.07  5003.5 2045.57  5003.8 2045.07
  5007.3 2045.07  5007.5 2045.57  5019.3 2046.43  5029.4 2052.85  5049.5 2054.79
  5059.6 2057.19  5089.8 2066.23  5096.6 2069.50  5101.6 2070.55  5109.9 2074.48
  5119.9 2077.98  5140.1 2083.70  5160.2 2086.02  5192.7 2088.35  5197.2 2089.35
#Mann=5,-1,0
  4841.8   0.035       0  4848.1    0.07       0  5001.5    0.16       0
  5003.5    0.07       0  5007.5    0.16       0
Bank Sta=5003.5,5007.5
Exp/Cntr=0.3,0.1

Type RM Length L Ch R = 1,2840,92,92,92
BEGIN DESCRIPTION:
Elm 84 2840.159
END DESCRIPTION:
XS GIS Cut Line= 3
      1533064.98      6768032.71      1533247.41      6768038.01
      1533418.74      6768028.37
#Sta/Elev= 30
  4817.5 2086.75  4820.0 2086.75  4825.0 2085.56  4830.0 2087.18  4837.5 2086.43
  4847.5 2083.08  4867.5 2074.67  4877.5 2070.98  4887.5 2068.06  4897.5 2065.80
  4941.0 2057.90  4957.6 2054.18  4967.6 2052.98  4977.6 2050.71  4987.6 2044.67
  4994.3 2043.73  4994.5 2043.23  4998.0 2043.23  4998.3 2043.73  5007.6 2044.14
  5017.6 2049.75  5037.7 2058.21  5047.7 2063.73  5086.0 2083.44  5097.7 2084.76
  5107.8 2084.16  5127.8 2081.61  5137.8 2081.75  5167.2 2088.72  5171.6 2088.72
#Mann=4,-1,0
  4817.5    0.07       0  4941.0    0.16       0  4994.3    0.07       0
  4998.3    0.16       0
Bank Sta=4994.3,4998.3
Exp/Cntr=0.3,0.1

Type RM Length L Ch R = 1,2748,71,71,71
BEGIN DESCRIPTION:
Elm 84 2748.1
END DESCRIPTION:
XS GIS Cut Line= 3
      1533078.00      6768093.47      1533212.56      6768117.35
      1533441.29      6768054.77
#Sta/Elev= 30
  4869.5 2087.93  4886.8 2086.44  4896.9 2083.33  4917.2 2075.10  4923.2 2070.23
  4928.3 2072.25  4966.4 2053.86  4977.2 2045.92  4982.3 2046.44  4988.3 2041.85
  5002.9 2041.14  5003.1 2040.64  5006.9 2041.14  5018.3 2043.12  5023.4 2042.16
  5029.4 2046.63  5057.9 2054.28  5063.1 2052.12  5070.9 2056.95  5081.3 2060.74
  5112.4 2069.55  5132.1 2069.14  5137.3 2072.65  5164.2 2070.44  5184.9 2079.77
  5205.7 2085.72  5216.7 2087.62  5226.4 2087.60  5236.8 2089.46  5243.3 2092.17
#Mann=4,-1,0
  4869.5    0.07       0  4966.4    0.16       0  5002.9    0.07       0
  5006.9    0.16       0
Bank Sta=5002.9,5006.9
Exp/Cntr=0.3,0.1

Type RM Length L Ch R = 1,2677,65,65,65
BEGIN DESCRIPTION:
Elm 84 2676.67
END DESCRIPTION:
XS GIS Cut Line= 3
      1533093.16      6768169.43      1533245.11      6768175.94
      1533429.54      6768145.56
#Sta/Elev= 30
  4851.8 2085.41  4855.2 2085.41  4863.6 2083.42  4913.7 2059.56  4923.7 2056.25
  4937.0 2052.81  4953.7 2042.97  4956.5 2042.29  4963.7 2040.54  4971.7 2039.97
  4972.0 2039.47  4975.5 2039.47  4975.7 2039.97  4993.8 2040.20  5001.3 2041.23
  5006.4 2041.23  5013.9 2044.00  5025.5 2045.61  5034.2 2050.60  5044.3 2055.34
  5074.7 2067.44  5081.6 2071.09  5086.7 2068.82  5095.0 2073.03  5115.3 2081.74
  5125.4 2085.29  5135.5 2087.49  5142.8 2088.26  5188.4 2090.11  5190.8 2090.11
#Mann=5,-1,0
  4851.8    0.07       0  4956.5    0.16       0  4971.7    0.07       0
  4975.7    0.16       0  5188.4    0.07       0
Bank Sta=4971.7,4975.7
Exp/Cntr=0.3,0.1

Type RM Length L Ch R = 1,2612,105,105,105
BEGIN DESCRIPTION:
Elm 84 2612.12
END DESCRIPTION:
XS GIS Cut Line= 3
      1533084.56      6768223.69      1533255.96      6768236.70
      1533440.22      6768195.52
#Sta/Elev= 30
  4832.7 2085.55  4843.2 2085.90  4853.2 2084.55  4863.2 2080.85  4883.3 2071.03
  4923.4 2052.75  4933.4 2049.59  4943.5 2047.41  4971.2 2042.82  4973.5 2042.55
  4981.6 2039.38  4981.8 2038.88  4985.3 2038.88  4985.6 2039.38  4993.6 2039.43
  5001.6 2043.88  5006.7 2043.88  5020.3 2054.39  5025.4 2053.42  5034.3 2056.17
  5044.6 2058.44  5063.7 2061.62  5075.3 2065.98  5106.1 2072.83  5112.2 2075.69
  5117.3 2076.30  5136.8 2082.76  5147.1 2085.55  5155.6 2087.35  5193.4 2089.77
#Mann=4,-1,0
  4832.7    0.07       0  4971.2    0.16       0  4981.6    0.07       0
  4985.6    0.16       0
Bank Sta=4981.6,4985.6
Exp/Cntr=0.3,0.1

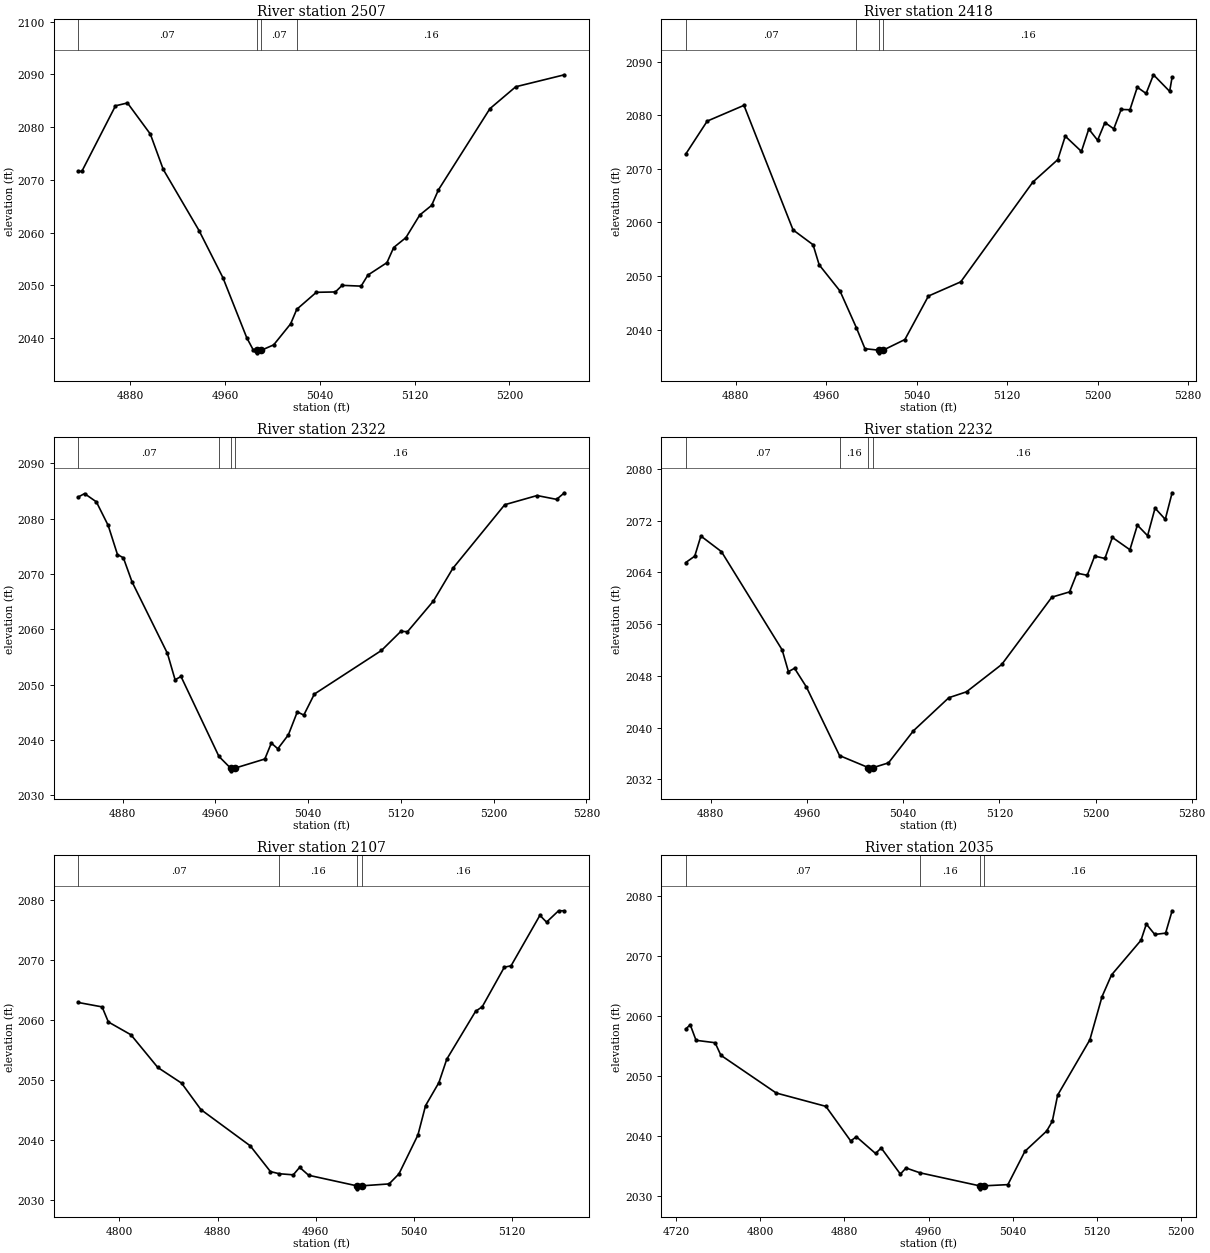
Type RM Length L Ch R = 1,2507,89,89,89
BEGIN DESCRIPTION:
Elm 84 2506.63
END DESCRIPTION:
XS GIS Cut Line= 3
      1533073.64      6768340.87      1533234.26      6768321.34
      1533451.76      6768200.74
#Sta/Elev= 30
  4835.9 2071.62  4839.1 2071.62  4867.5 2084.04  4877.6 2084.58  4896.9 2078.69
  4907.8 2071.99  4938.0 2060.41  4958.2 2051.45  4978.3 2040.08  4983.6 2037.85
  4986.7 2037.73  4986.9 2037.23  4990.7 2037.73  5001.0 2038.74  5015.3 2042.72
  5020.5 2045.48  5037.0 2048.70  5053.1 2048.77  5058.8 2050.02  5074.8 2049.87
  5080.5 2051.96  5096.6 2054.32  5102.3 2057.19  5112.6 2059.06  5124.3 2063.35
  5134.3 2065.17  5140.1 2068.13  5183.5 2083.50  5205.3 2087.65  5246.4 2089.92
#Mann=4,-1,0
  4835.9    0.07       0  4986.7    0.07       0  4990.7    0.07       0
  5020.5    0.16       0
Bank Sta=4986.7,4990.7
Exp/Cntr=0.3,0.1

Type RM Length L Ch R = 1,2418,96,96,96
BEGIN DESCRIPTION:
Elm 84 2418.1
END DESCRIPTION:
XS GIS Cut Line= 3
      1533147.50      6768447.19      1533297.19      6768384.27
      1533501.98      6768211.82
#Sta/Elev= 30
  4835.7 2072.74  4854.7 2078.89  4887.2 2081.83  4930.6 2058.60  4948.3 2055.83
  4953.7 2052.08  4972.1 2047.21  4986.6 2040.35  4994.2 2036.44  5006.3 2036.17
  5006.5 2035.67  5010.3 2036.17  5029.5 2038.15  5050.3 2046.26  5078.9 2048.91
  5142.7 2067.53  5164.7 2071.71  5171.3 2076.08  5185.6 2073.23  5192.1 2077.41
  5199.9 2075.32  5206.4 2078.62  5214.2 2077.45  5220.7 2081.06  5228.5 2081.01
  5235.0 2085.21  5242.8 2084.04  5249.3 2087.53  5263.6 2084.44  5265.8 2087.09
#Mann=4,-1,0
  4835.7    0.07       0  4986.6    0.16       0  5006.3    0.07       0
  5010.3    0.16       0
Bank Sta=5006.3,5010.3
Exp/Cntr=0.3,0.1

Type RM Length L Ch R = 1,2322,90,90,90
BEGIN DESCRIPTION:
Elm 84 2322.32
END DESCRIPTION:
XS GIS Cut Line= 3
      1533199.53      6768490.61      1533353.62      6768458.06
      1533587.96      6768340.88
#Sta/Elev= 30
  4841.5 2083.91  4847.1 2084.54  4857.3 2083.05  4867.5 2078.78  4875.5 2073.52
  4880.6 2072.93  4888.0 2068.61  4918.6 2055.64  4925.2 2050.88  4930.3 2051.47
  4963.0 2037.02  4973.0 2034.91  4973.2 2034.41  4977.0 2034.91  5002.6 2036.55
  5008.2 2039.43  5013.8 2038.40  5022.9 2040.92  5030.6 2045.07  5036.2 2044.49
  5045.3 2048.29  5103.2 2056.18  5120.0 2059.65  5125.6 2059.56  5148.0 2065.12
  5164.7 2071.01  5209.5 2082.53  5237.4 2084.19  5254.2 2083.50  5261.0 2084.69
#Mann=4,-1,0
  4841.5    0.07       0  4963.0    0.16       0  4973.0    0.07       0
  4977.0    0.16       0
Bank Sta=4973,4977
Exp/Cntr=0.3,0.1

Type RM Length L Ch R = 1,2232,125,125,125
BEGIN DESCRIPTION:
Elm 84 2231.89
END DESCRIPTION:
XS GIS Cut Line= 3
      1533225.54      6768564.40      1533370.98      6768544.86
      1533579.25      6768393.00
#Sta/Elev= 30
  4859.2 2065.51  4866.7 2066.50  4871.8 2069.61  4888.9 2067.20  4939.4 2052.00
  4944.6 2048.64  4949.7 2049.16  4959.6 2046.25  4987.1 2035.66  5011.1 2033.80
  5011.4 2033.30  5015.1 2033.80  5027.8 2034.53  5048.6 2039.50  5078.0 2044.61
  5092.7 2045.52  5122.0 2049.75  5163.7 2060.16  5178.4 2060.97  5184.6 2063.87
  5193.1 2063.54  5199.3 2066.51  5207.8 2066.14  5214.0 2069.40  5228.6 2067.49
  5234.8 2071.30  5243.3 2069.66  5249.5 2073.93  5258.0 2072.19  5263.7 2076.30
#Mann=4,-1,0
  4859.2    0.07       0  4987.1    0.16       0  5011.1    0.07       0
  5015.1    0.16       0
Bank Sta=5011.1,5015.1
Exp/Cntr=0.3,0.1

Type RM Length L Ch R = 1,2107,72,72,72
BEGIN DESCRIPTION:
Elm 84 2107.06
END DESCRIPTION:
XS GIS Cut Line= 3
      1533223.37      6768577.41      1533453.44      6768638.18
      1533598.84      6768575.24
#Sta/Elev= 30
  4766.3 2062.89  4785.9 2062.15  4791.0 2059.64  4809.4 2057.51  4831.3 2052.07
  4850.7 2049.46  4866.4 2045.07  4906.6 2039.04  4923.1 2034.75  4930.4 2034.39
  4941.7 2034.21  4946.9 2035.46  4954.2 2034.14  4993.5 2032.38  4993.8 2031.88
  4997.5 2032.38  5019.8 2032.70  5027.8 2034.36  5043.3 2040.84  5049.5 2045.72
  5060.4 2049.56  5066.8 2053.45  5090.3 2061.42  5095.7 2062.17  5113.7 2068.75
  5119.2 2068.99  5142.7 2077.38  5148.1 2076.25  5157.9 2078.14  5162.7 2078.14
#Mann=4,-1,0
  4766.3    0.07       0  4930.4    0.16       0  4993.5    0.07       0
  4997.5    0.16       0
Bank Sta=4993.5,4997.5
Exp/Cntr=0.3,0.1

Type RM Length L Ch R = 1,2035,119,119,119
BEGIN DESCRIPTION:
Elm 84 2035.46
END DESCRIPTION:
XS GIS Cut Line= 3
      1533206.05      6768601.29      1533459.95      6768709.79
      1533641.08      6768666.67
#Sta/Elev= 30
  4729.1 2057.86  4733.4 2058.55  4738.9 2055.97  4757.0 2055.57  4762.5 2053.48
  4815.1 2047.20  4862.3 2044.98  4885.9 2039.22  4891.3 2039.92  4909.5 2037.14
  4914.9 2038.05  4933.1 2033.71  4938.5 2034.72  4951.7 2033.92  5008.4 2031.75
  5008.7 2031.25  5012.4 2031.75  5035.3 2031.95  5051.5 2037.50  5072.1 2040.86
  5077.5 2042.48  5082.6 2046.85  5113.2 2056.05  5124.8 2063.25  5133.8 2066.85
  5161.8 2072.62  5166.9 2075.32  5174.9 2073.59  5185.2 2073.81  5191.4 2077.53
#Mann=4,-1,0
  4729.1    0.07       0  4951.7    0.16       0  5008.4    0.07       0
  5012.4    0.16       0
Bank Sta=5008.4,5012.4
Exp/Cntr=0.3,0.1

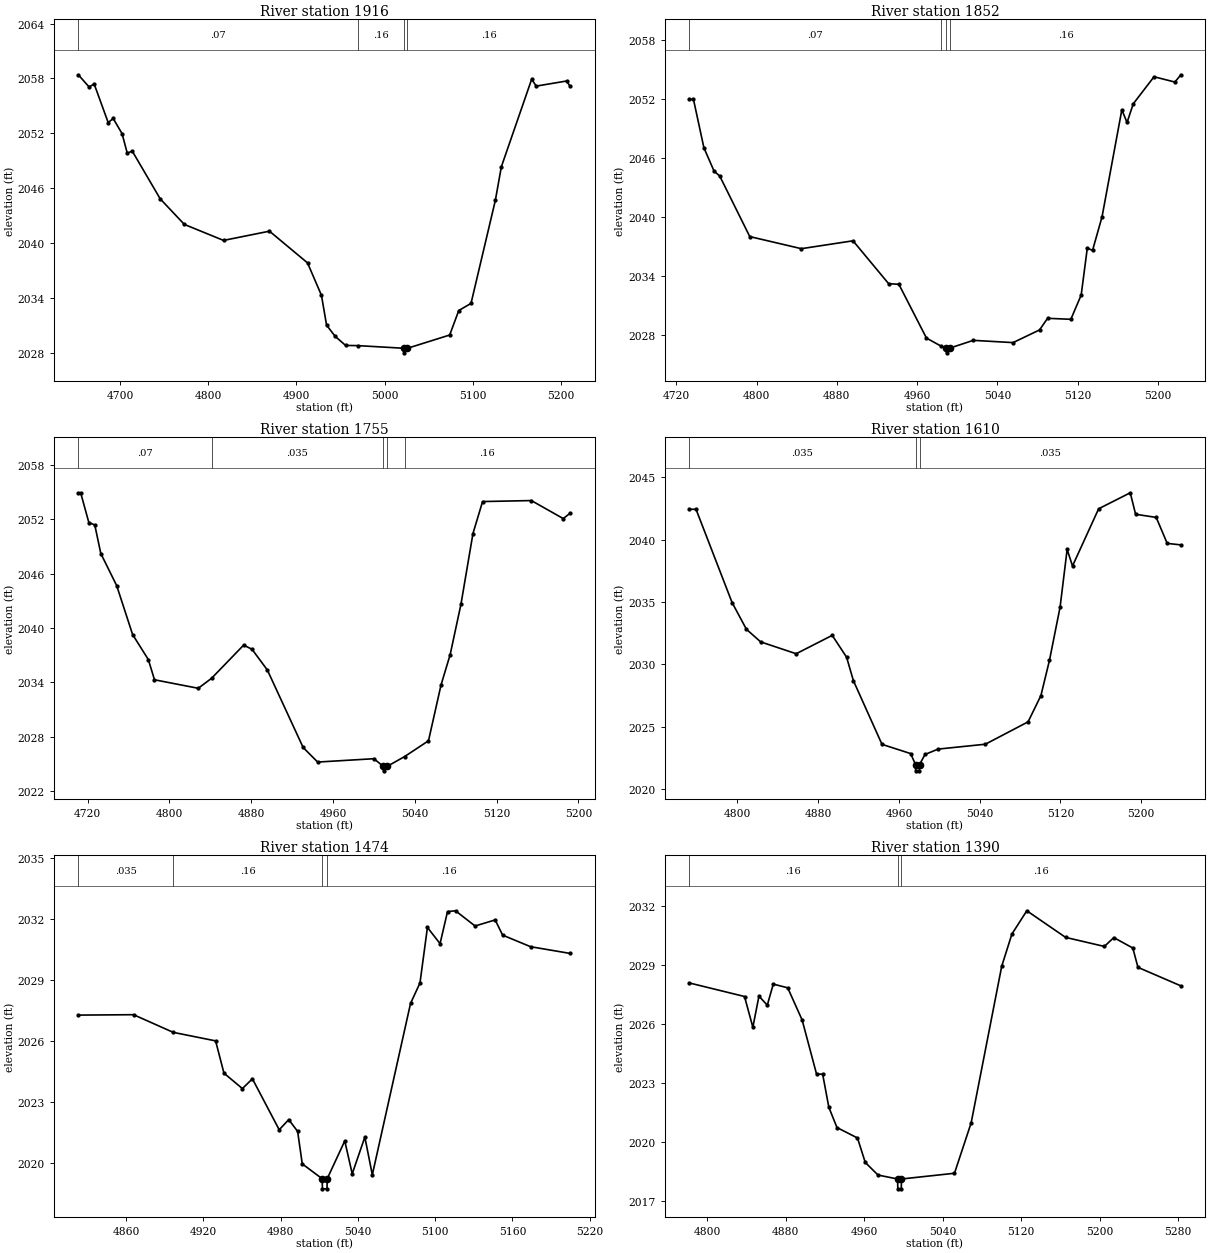
Type RM Length L Ch R = 1,1916,64,64,64
BEGIN DESCRIPTION:
Elm 84 1915.703
END DESCRIPTION:
XS GIS Cut Line= 3
      1533151.81      6768655.55      1533453.78      6768827.50
      1533656.68      6768883.20
#Sta/Elev= 30
  4652.5 2058.40  4664.7 2057.07  4670.5 2057.39  4686.4 2053.17  4692.1 2053.62
  4702.2 2051.95  4708.0 2049.83  4713.7 2050.05  4745.4 2044.83  4772.8 2042.03
  4817.3 2040.28  4869.4 2041.29  4912.6 2037.82  4928.4 2034.27  4934.2 2031.01
  4943.9 2029.79  4955.8 2028.79  4969.5 2028.77  5022.0 2028.48  5022.2 2027.98
  5026.0 2028.48  5073.9 2029.93  5084.2 2032.61  5098.1 2033.39  5125.7 2044.66
  5132.5 2048.33  5166.9 2057.91  5172.1 2057.16  5206.6 2057.72  5210.4 2057.15
#Mann=4,-1,0
  4652.5    0.07       0  4969.5    0.16       0  5022.0    0.07       0
  5026.0    0.16       0
Bank Sta=5022,5026
Exp/Cntr=0.3,0.1

Type RM Length L Ch R = 1,1852,97,97,97
BEGIN DESCRIPTION:
Elm 84 4220
END DESCRIPTION:
XS GIS Cut Line= 3
      1533182.18      6768748.86      1533415.90      6768878.37
      1533630.71      6768937.47
#Sta/Elev= 30
  4732.8 2051.95  4737.1 2051.95  4747.5 2047.03  4757.6 2044.66  4763.3 2044.15
  4793.2 2038.00  4844.6 2036.77  4896.1 2037.57  4931.6 2033.21  4941.8 2033.15
  4969.3 2027.68  4983.9 2026.86  4989.1 2026.68  4989.3 2026.18  4993.1 2026.68
  5016.0 2027.45  5055.6 2027.22  5082.0 2028.51  5090.0 2029.69  5113.2 2029.59
  5123.5 2032.06  5129.6 2036.84  5134.8 2036.59  5144.3 2040.02  5164.0 2050.89
  5169.2 2049.60  5175.4 2051.50  5196.1 2054.25  5216.9 2053.71  5222.8 2054.45
#Mann=4,-1,0
  4732.8    0.07       0  4983.9    0.16       0  4989.1    0.07       0
  4993.1    0.16       0
Bank Sta=4989.1,4993.1
Exp/Cntr=0.3,0.1

Type RM Length L Ch R = 1,1755,145,145,145
BEGIN DESCRIPTION:
Elm 84 4219
END DESCRIPTION:
XS GIS Cut Line= 3
      1533156.12      6768824.80      1533404.48      6768972.78
      1533585.80      6769035.31
#Sta/Elev= 30
  4710.9 2054.94  4713.2 2054.94  4721.2 2051.65  4727.0 2051.39  4732.9 2048.23
  4748.4 2044.69  4764.0 2039.28  4779.4 2036.51  4785.4 2034.28  4828.2 2033.34
  4841.2 2034.44  4872.6 2038.11  4880.8 2037.65  4895.8 2035.36  4930.8 2026.80
  4945.0 2025.19  5000.0 2025.56  5009.1 2024.72  5009.4 2024.22  5013.1 2024.72
  5030.1 2025.80  5053.4 2027.54  5065.7 2033.72  5074.6 2037.06  5085.2 2042.65
  5096.9 2050.44  5106.3 2053.97  5154.0 2054.08  5185.2 2052.09  5191.8 2052.67
#Mann=5,-1,0
  4710.9    0.07       0  4841.2   0.035       0  5009.1   0.035       0
  5013.1   0.035       0  5030.1    0.16       0
Bank Sta=5009.1,5013.1
Exp/Cntr=0.3,0.1

Type RM Length L Ch R = 1,1610,136,136,136
BEGIN DESCRIPTION:
Elm 84 4214
END DESCRIPTION:
XS GIS Cut Line= 3
      1533130.03      6768913.02      1533311.83      6769081.40
      1533538.09      6769159.02
#Sta/Elev= 30
  4752.2 2042.42  4759.0 2042.42  4794.7 2034.96  4808.9 2032.82  4823.0 2031.81
  4858.2 2030.86  4893.9 2032.33  4908.1 2030.59  4914.9 2028.70  4943.2 2023.61
  4971.6 2022.87  4976.4 2021.99  4976.6 2021.49  4980.1 2021.49  4980.4 2021.99
  4985.8 2022.80  4998.8 2023.23  5045.6 2023.62  5087.9 2025.41  5100.6 2027.51
  5109.1 2030.34  5119.6 2034.59  5126.6 2039.21  5131.9 2037.88  5157.8 2042.46
  5189.1 2043.74  5194.4 2042.02  5214.8 2041.77  5225.7 2039.69  5239.2 2039.57
#Mann=3,-1,0
  4752.2   0.035       0  4976.4   0.035       0  4980.4   0.035       0
Bank Sta=4976.4,4980.4
Exp/Cntr=0.3,0.1

Type RM Length L Ch R = 1,1474,84,84,84
BEGIN DESCRIPTION:
Elm 84 4213
END DESCRIPTION:
XS GIS Cut Line= 3
      1533080.02      6769063.02      1533215.49      6769177.09
      1533391.32      6769281.90
#Sta/Elev= 30
  4822.9 2027.27  4865.8 2027.29  4896.6 2026.42  4929.5 2026.00  4936.0 2024.41
  4950.3 2023.65  4958.1 2024.13  4978.9 2021.62  4986.3 2022.12  4993.2 2021.54
  4996.8 2019.94  5012.2 2019.21  5012.5 2018.71  5016.0 2018.71  5016.2 2019.21
  5029.8 2021.07  5035.6 2019.45  5045.4 2021.26  5051.2 2019.40  5080.9 2027.85
  5088.2 2028.85  5094.0 2031.59  5103.8 2030.79  5109.6 2032.37  5115.8 2032.41
  5131.0 2031.66  5146.6 2031.96  5152.4 2031.21  5174.1 2030.64  5204.7 2030.31
#Mann=4,-1,0
  4822.9   0.035       0  4896.6    0.16       0  5012.2    0.07       0
  5016.2    0.16       0
Bank Sta=5012.2,5016.2
Exp/Cntr=0.3,0.1

Type RM Length L Ch R = 1,1390,102,102,102
BEGIN DESCRIPTION:
Elm 84 4218
END DESCRIPTION:
XS GIS Cut Line= 3
      1533030.01      6769063.01      1533158.53      6769239.46
      1533430.85      6769315.01
#Sta/Elev= 30
  4781.7 2028.08  4838.1 2027.39  4846.6 2025.83  4852.8 2027.41  4861.3 2026.95
  4867.4 2028.02  4882.1 2027.83  4896.8 2026.20  4911.5 2023.45  4917.7 2023.45
  4924.0 2021.77  4932.3 2020.74  4953.2 2020.21  4961.1 2018.97  4974.1 2018.33
  4994.0 2018.13  4994.3 2017.63  4997.8 2017.63  4998.0 2018.13  5052.0 2018.42
  5069.0 2020.98  5100.1 2028.92  5110.5 2030.56  5125.7 2031.74  5165.2 2030.39
  5204.7 2029.93  5214.3 2030.38  5233.7 2029.85  5238.9 2028.87  5282.6 2027.93
#Mann=3,-1,0
  4781.7    0.16       0  4994.0    0.07       0  4998.0    0.16       0
Bank Sta=4994,4998
Exp/Cntr=0.3,0.1

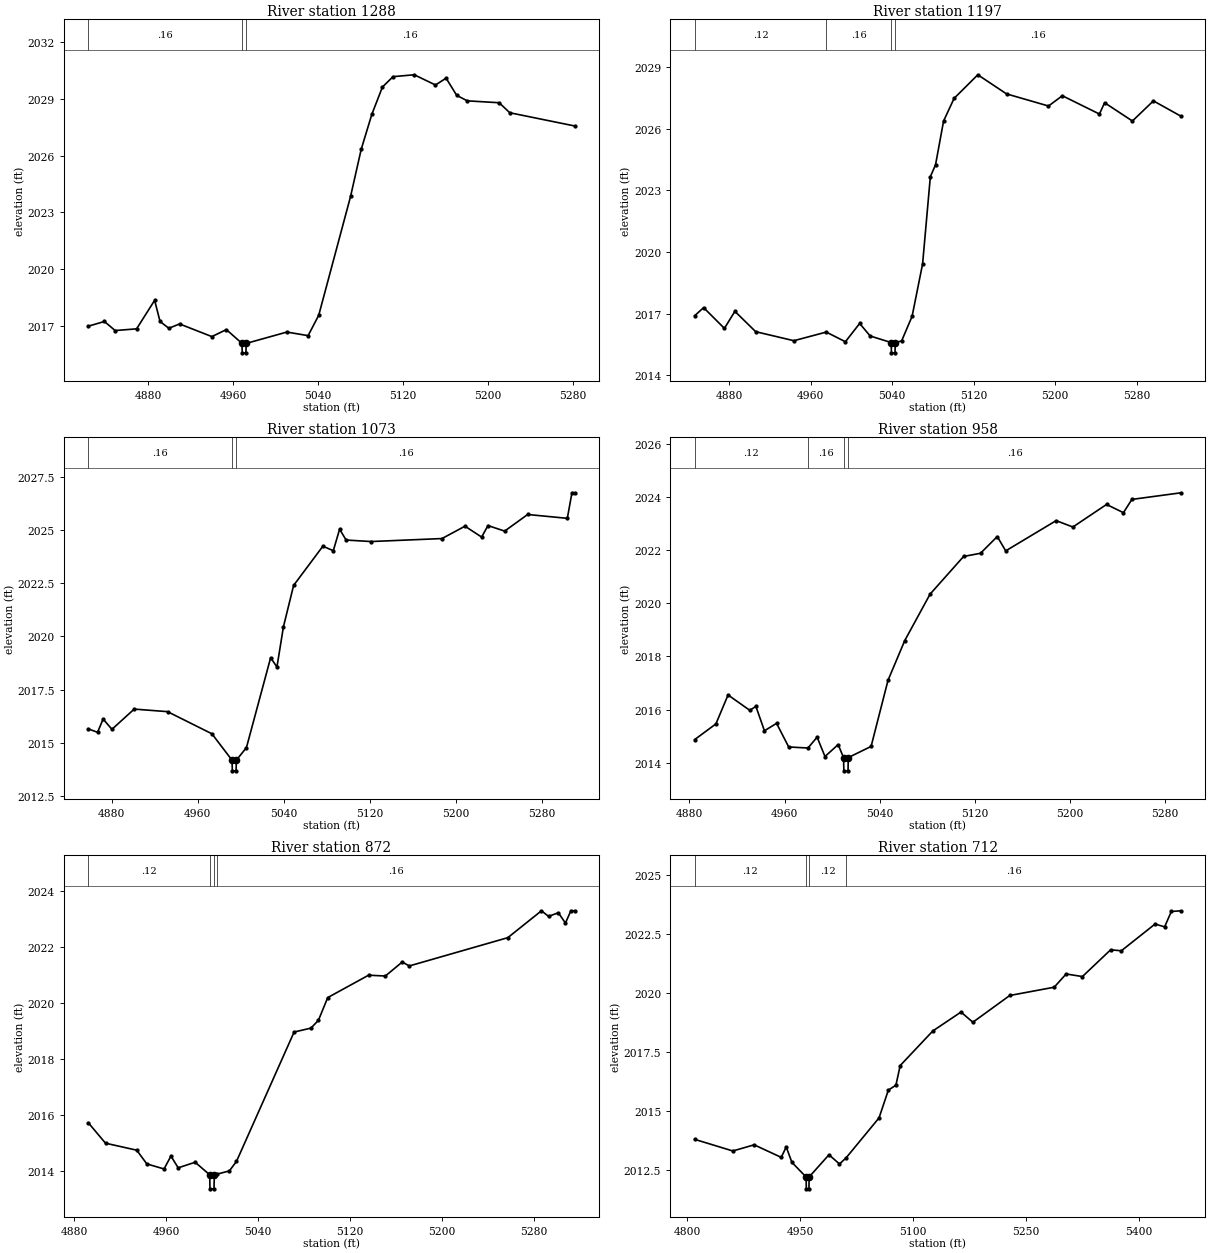
Type RM Length L Ch R = 1,1288,91,91,91
BEGIN DESCRIPTION:
Elm 84 4217
END DESCRIPTION:
XS GIS Cut Line= 3
      1532980.02      6769313.00      1533154.57      6769340.47
      1533436.05      6769336.96
#Sta/Elev= 30
  4823.3 2016.97  4838.5 2017.22  4848.6 2016.74  4868.8 2016.83  4885.8 2018.34
  4890.9 2017.22  4899.2 2016.86  4909.3 2017.09  4939.7 2016.42  4953.4 2016.79
  4968.1 2016.06  4968.3 2015.56  4971.8 2015.56  4972.1 2016.06  5010.4 2016.66
  5030.4 2016.47  5040.4 2017.55  5070.4 2023.84  5080.4 2026.33  5090.4 2028.18
  5100.4 2029.63  5110.4 2030.18  5130.4 2030.28  5150.4 2029.74  5160.4 2030.10
  5170.4 2029.19  5180.4 2028.90  5210.4 2028.80  5220.4 2028.27  5281.5 2027.57
#Mann=3,-1,0
  4823.3    0.16       0  4968.1    0.07       0  4972.1    0.16       0
Bank Sta=4968.1,4972.1
Exp/Cntr=0.3,0.1

Type RM Length L Ch R = 1,1197,124,124,124
BEGIN DESCRIPTION:
Elm 84 4216
END DESCRIPTION:
XS GIS Cut Line= 3
      1533006.44      6769462.82      1533157.24      6769432.07
      1533471.45      6769354.70
#Sta/Elev= 30
  4846.1 2016.90  4854.8 2017.29  4875.2 2016.28  4885.5 2017.11  4905.9 2016.12
  4943.4 2015.68  4975.2 2016.10  4994.0 2015.63  5008.0 2016.52  5018.3 2015.91
  5039.0 2015.59  5039.2 2015.09  5042.7 2015.09  5043.0 2015.59  5049.2 2015.67
  5059.5 2016.87  5069.8 2019.42  5077.4 2023.66  5082.5 2024.24  5090.4 2026.37
  5100.7 2027.47  5124.0 2028.62  5152.2 2027.69  5193.4 2027.10  5207.0 2027.60
  5243.4 2026.71  5248.5 2027.26  5275.8 2026.37  5296.4 2027.35  5323.6 2026.60
#Mann=4,-1,0
  4846.1    0.12       0  4975.2    0.16       0  5039.0    0.07       0
  5043.0    0.16       0
Bank Sta=5039,5043
Exp/Cntr=0.3,0.1

Type RM Length L Ch R = 1,1073,115,115,115
BEGIN DESCRIPTION:
Elm 84 4215
END DESCRIPTION:
XS GIS Cut Line= 3
      1533073.68      6769575.68      1533211.08      6769540.20
      1533477.29      6769380.38
#Sta/Elev= 30
  4858.1 2015.66  4866.7 2015.50  4871.9 2016.12  4880.1 2015.64  4900.8 2016.59
  4931.8 2016.47  4973.1 2015.43  4991.8 2014.19  4992.1 2013.69  4995.6 2013.69
  4995.8 2014.19  5005.2 2014.78  5027.7 2019.00  5033.6 2018.57  5039.6 2020.45
  5049.1 2022.40  5076.3 2024.24  5086.0 2024.03  5091.9 2025.04  5097.9 2024.53
  5121.2 2024.46  5187.1 2024.60  5208.5 2025.18  5224.0 2024.67  5229.9 2025.21
  5245.4 2024.95  5266.8 2025.73  5303.7 2025.55  5308.0 2026.75  5310.5 2026.75
#Mann=3,-1,0
  4858.1    0.16       0  4991.8    0.07       0  4995.8    0.16       0
Bank Sta=4991.8,4995.8
Exp/Cntr=0.3,0.1

Type RM Length L Ch R = 1,958,86,86,86
BEGIN DESCRIPTION:
Elm 84 4212
END DESCRIPTION:
XS GIS Cut Line= 3
      1533147.50      6769662.48      1533260.85      6769640.29
      1533467.27      6769431.65
#Sta/Elev= 30
  4884.5 2014.87  4902.3 2015.46  4912.5 2016.55  4930.8 2015.97  4935.9 2016.12
  4943.1 2015.20  4953.3 2015.48  4963.5 2014.59  4979.7 2014.55  4987.4 2014.96
  4994.0 2014.23  5005.1 2014.68  5009.6 2014.19  5009.9 2013.69  5013.4 2013.69
  5013.6 2014.19  5032.8 2014.61  5047.0 2017.10  5061.1 2018.60  5082.4 2020.35
  5110.6 2021.77  5124.8 2021.89  5138.9 2022.52  5146.0 2021.98  5188.4 2023.12
  5202.5 2022.88  5230.8 2023.73  5245.0 2023.42  5252.1 2023.92  5293.5 2024.17
#Mann=4,-1,0
  4884.5    0.12       0  4979.7    0.16       0  5009.6    0.07       0
  5013.6    0.16       0
Bank Sta=5009.6,5013.6
Exp/Cntr=0.3,0.1

Type RM Length L Ch R = 1,872,160,160,160
BEGIN DESCRIPTION:
Elm 84 4211
END DESCRIPTION:
XS GIS Cut Line= 3
      1533229.97      6769763.02      1533319.54      6769702.85
      1533505.53      6769447.63
#Sta/Elev= 30
  4892.1 2015.74  4907.1 2015.01  4934.3 2014.76  4943.1 2014.27  4958.1 2014.09
  4964.1 2014.55  4970.4 2014.13  4985.2 2014.33  4997.9 2013.88  4998.1 2013.38
  5001.6 2013.38  5001.9 2013.88  5003.8 2013.90  5015.0 2014.02  5021.2 2014.36
  5071.4 2018.98  5086.1 2019.12  5092.6 2019.40  5100.7 2020.21  5136.3 2021.01
  5150.9 2020.98  5165.6 2021.48  5171.8 2021.34  5257.6 2022.35  5286.9 2023.31
  5293.1 2023.11  5301.6 2023.24  5307.8 2022.87  5312.5 2023.31  5315.8 2023.31
#Mann=4,-1,0
  4892.1    0.12       0  4997.9    0.07       0  5001.9    0.12       0
  5003.8    0.16       0
Bank Sta=4997.9,5001.9
Exp/Cntr=0.3,0.1

Type RM Length L Ch R = 1,712,106,106,106
BEGIN DESCRIPTION:
Elm 84 4208
END DESCRIPTION:
XS GIS Cut Line= 3
      1533258.10      6769963.03      1533399.23      6769835.68
      1533624.88      6769438.96
#Sta/Elev= 30
  4809.9 2013.81  4860.5 2013.32  4888.9 2013.58  4924.8 2013.05  4931.5 2013.49
  4939.0 2012.84  4957.9 2012.22  4958.2 2011.72  4961.7 2011.72  4961.9 2012.22
  4988.3 2013.16  5002.3 2012.77  5011.1 2013.03  5054.9 2014.72  5067.2 2015.89
  5077.3 2016.10  5083.0 2016.93  5126.3 2018.39  5163.8 2019.19  5179.6 2018.76
  5228.6 2019.89  5287.7 2020.24  5303.6 2020.80  5325.2 2020.69  5362.7 2021.82
  5377.0 2021.78  5421.8 2022.91  5434.5 2022.79  5443.4 2023.44  5456.4 2023.47
#Mann=4,-1,0
  4809.9    0.12       0  4957.9    0.07       0  4961.9    0.12       0
  5011.1    0.16       0
Bank Sta=4957.9,4961.9
Exp/Cntr=0.3,0.1

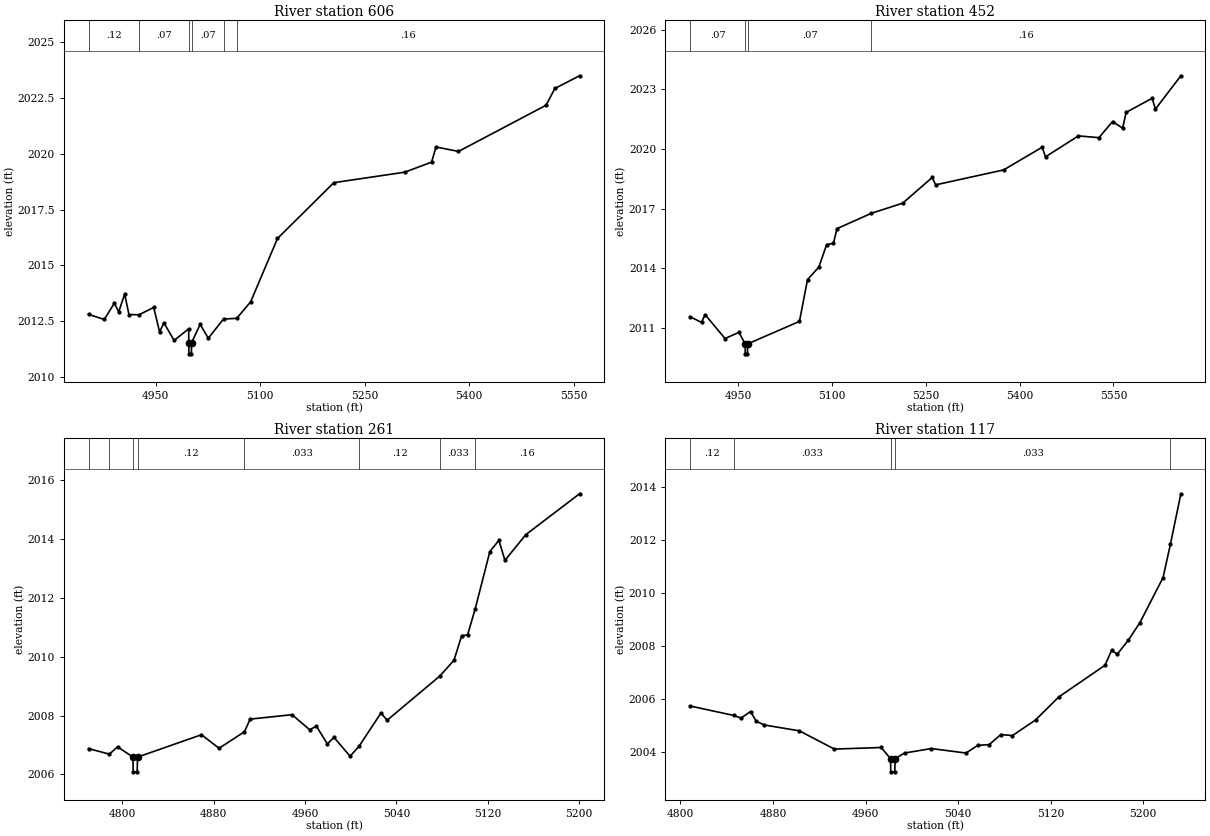
Type RM Length L Ch R = 1,606,154,154,154
BEGIN DESCRIPTION:
Elm 84 4209
END DESCRIPTION:
XS GIS Cut Line= 3
      1533292.87      6770027.05      1533410.52      6769940.43
      1533668.31      6769445.43
#Sta/Elev= 30
  4853.9 2012.81  4876.4 2012.58  4891.0 2013.31  4897.2 2012.92  4905.7 2013.72
  4911.9 2012.80  4926.3 2012.79  4947.4 2013.12  4955.8 2012.02  4962.0 2012.43
  4976.7 2011.64  4997.5 2012.16  4997.7 2011.54  4997.9 2011.04  5001.4 2011.04
  5001.7 2011.54  5014.0 2012.36  5025.7 2011.74  5047.5 2012.60  5066.4 2012.63
  5086.4 2013.37  5124.9 2016.21  5205.7 2018.71  5307.4 2019.18  5345.9 2019.63
  5352.3 2020.31  5384.5 2020.11  5510.1 2022.18  5522.7 2022.93  5558.1 2023.50
#Mann=6,-1,0
  4853.9    0.12       0  4926.3    0.07       0  4997.7    0.07       0
  5001.7    0.07       0  5047.5    0.12       0  5066.4    0.16       0
Bank Sta=4997.7,5001.7
Exp/Cntr=0.3,0.1

Type RM Length L Ch R = 1,452,191,191,191
BEGIN DESCRIPTION:
Elm 84 4210
END DESCRIPTION:
XS GIS Cut Line= 3
      1533405.69      6770113.01      1533517.34      6770052.07
      1533776.81      6769447.61
#Sta/Elev= 30
  4872.8 2011.58  4891.4 2011.29  4897.1 2011.68  4929.0 2010.48  4951.2 2010.79
  4961.2 2010.21  4961.4 2009.71  4964.9 2009.71  4965.2 2010.21  5048.0 2011.34
  5060.9 2013.44  5079.0 2014.07  5091.5 2015.20  5102.4 2015.26  5108.0 2016.00
  5162.9 2016.77  5213.1 2017.28  5260.2 2018.57  5265.7 2018.20  5374.4 2018.95
  5436.0 2020.09  5441.4 2019.61  5494.1 2020.66  5526.8 2020.57  5548.5 2021.38
  5564.7 2021.05  5570.3 2021.84  5611.8 2022.55  5617.2 2022.01  5657.8 2023.68
#Mann=4,-1,0
  4872.8    0.07       0  4961.2    0.07       0  4965.2    0.07       0
  5162.9    0.16       0
Bank Sta=4961.2,4965.2
Exp/Cntr=0.3,0.1

Type RM Length L Ch R = 1,261,144,144,144
BEGIN DESCRIPTION:
Elm 84 4205
END DESCRIPTION:
XS GIS Cut Line= 3
      1533425.21      6770324.39      1533620.94      6770204.37
      1533680.01      6770012.98
#Sta/Elev= 30
  4770.4 2006.88  4788.7 2006.69  4795.8 2006.94  4809.3 2006.59  4809.5 2006.09
  4813.0 2006.09  4813.3 2006.59  4869.3 2007.35  4884.7 2006.89  4906.9 2007.45
  4911.9 2007.88  4948.6 2008.03  4964.0 2007.52  4969.9 2007.64  4979.5 2007.04
  4985.3 2007.26  4999.4 2006.62  5007.3 2006.96  5026.5 2008.09  5031.8 2007.84
  5078.2 2009.35  5090.4 2009.88  5097.1 2010.71  5102.3 2010.74  5109.0 2011.63
  5121.8 2013.57  5129.7 2013.95  5135.0 2013.27  5153.2 2014.14  5200.3 2015.53
#Mann=8,-1,0
  4770.4   0.033       0  4788.7    0.12       0  4809.3   0.033       0
  4813.3    0.12       0  4906.9   0.033       0  5007.3    0.12       0
  5078.2   0.033       0  5109.0    0.16       0
Bank Sta=4809.3,4813.3
Exp/Cntr=0.3,0.1

Type RM Length L Ch R = 1,117,0,0,0
BEGIN DESCRIPTION:
Elm 84 4204
END DESCRIPTION:
XS GIS Cut Line= 3
      1533501.20      6770350.42      1533691.28      6770324.81
      1533702.99      6770092.60
#Sta/Elev= 30
  4808.2 2005.73  4846.3 2005.37  4852.4 2005.27  4860.6 2005.52  4865.6 2005.15
  4872.6 2005.01  4902.8 2004.79  4933.1 2004.10  4973.5 2004.16  4981.6 2003.74
  4981.8 2003.24  4985.3 2003.24  4985.6 2003.74  4993.7 2003.95  5016.8 2004.12
  5046.9 2003.95  5056.9 2004.24  5066.9 2004.27  5076.9 2004.65  5086.9 2004.61
  5106.9 2005.20  5127.0 2006.07  5167.0 2007.27  5172.6 2007.83  5177.6 2007.69
  5187.0 2008.21  5197.1 2008.88  5217.1 2010.58  5223.5 2011.85  5232.5 2013.75
#Mann=5,-1,0
  4808.2    0.12       0  4846.3   0.033       0  4981.6   0.033       0
  4985.6   0.033       0  5223.5    0.16       0
Bank Sta=4981.6,4985.6
Exp/Cntr=0.3,0.1

Chan Stop Cuts=-1