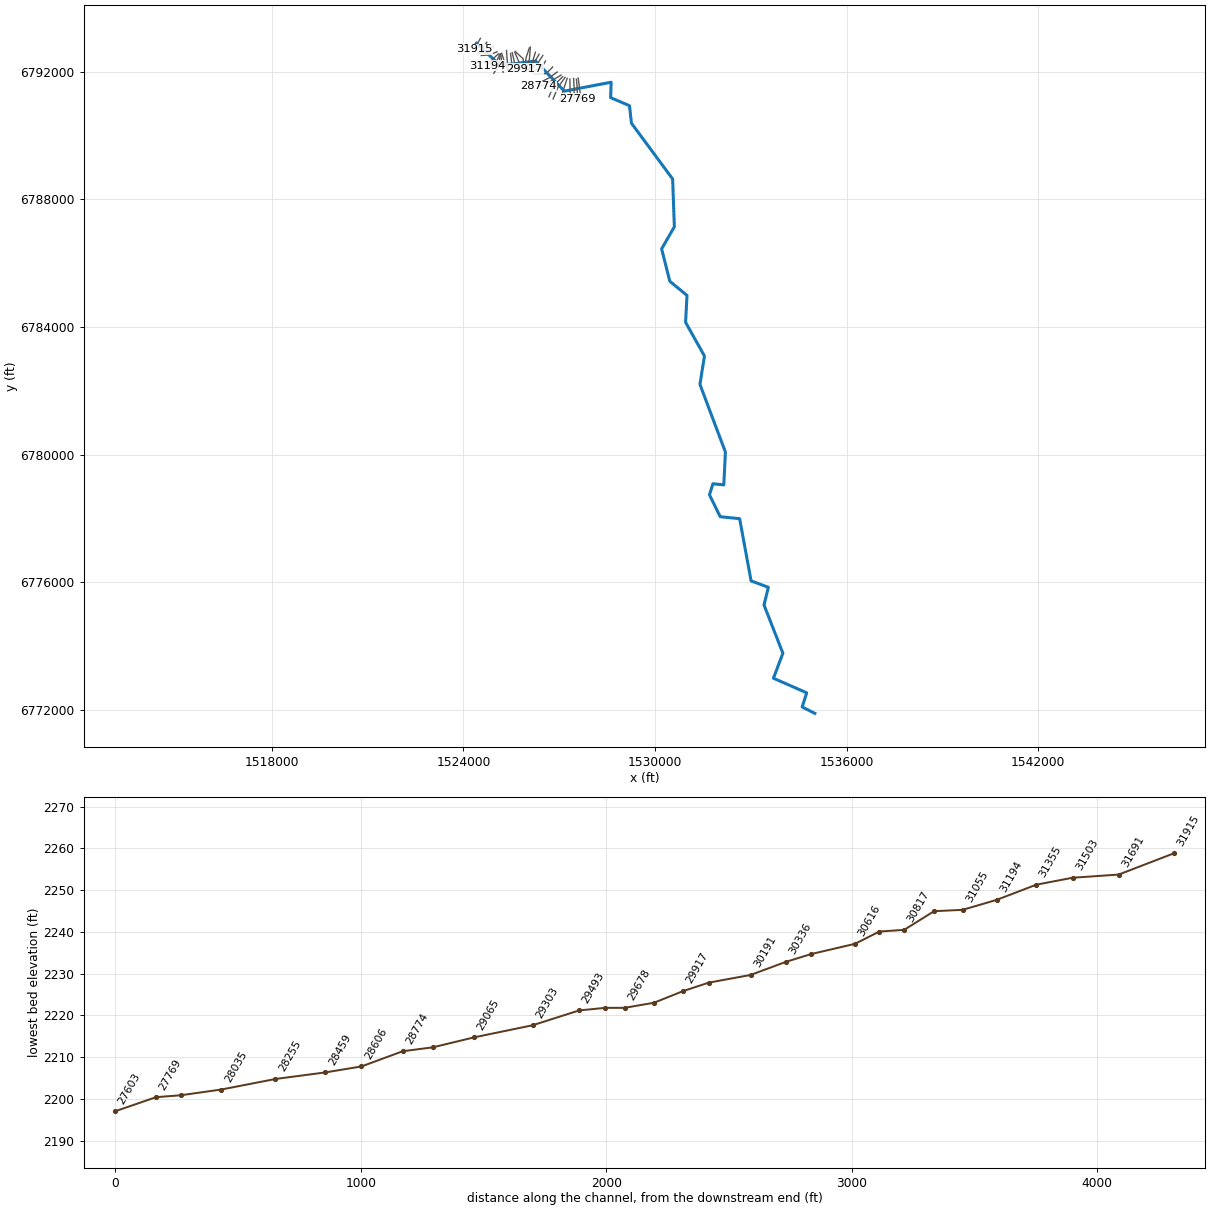
--- Elm 85.prj (project) ---

Proj Title=Elm 85 Base Level Engineering
Current Plan=p01
Default Exp/Contr=0.3,0.1
English Units
Geom File=g01
Flow File=f01
Plan File=p01
Y Axis Title=Elevation
X Axis Title(PF)=Main Channel Distance
X Axis Title(XS)=Station
BEGIN DESCRIPTION:
Elm 85
END DESCRIPTION:
DSS Export Rating Curves= 0
DSS Export Rating Curve Sorted= 0
DSS Export Volume Flow Curves= 0
DXF OffsetX= 0
DXF OffsetY= 0
DXF ScaleX= 1
DXF ScaleY= 10

--- Elm 85.p01 (plan) ---

Plan Title=Multiple Run
Program Version=4.10
Short Identifier=Multiple
Geom File=g01
Flow File=f01
Subcritical Flow
K Sum by GR= 0
Std Step Tol= 0.01
Critical Tol= 0.01
Num of Std Step Trials= 20
Max Error Tol= 0.3
Flow Tol Ratio= 0.001
Split Flow NTrial= 30
Split Flow Tol= 0.02
Split Flow Ratio= 0.02
Log Output Level= 0
Friction Slope Method= 1
Unsteady Friction Slope Method= 2
Unsteady Bridges Friction Slope Method= 1
Parabolic Critical Depth
Global Vel Dist= 1 , 1 , 1
Global Log Level= 0
CheckData=True
Encroach Param=-1 ,0,0, 0
BEGIN DESCRIPTION:
Multiple Run
END DESCRIPTION:
Computation Interval=1HOUR
Output Interval=1HOUR
Run HTab= 0
Run UNet= 0
Run PostProcess= 0
Run WQNet= 0
UNET Theta= 1
UNET Theta Warmup= 1
UNET ZTol= 0.02
UNET ZSATol= 0.05
UNET MxIter= 20
UNET MaxInSteps= 0
UNET DtIC= 0
UNET DtMin= 0
UNET MaxCRTS= 20
UNET WFStab= 2
UNET SFStab= 1
UNET WFX= 1
UNET SFX= 1
UNET DSS MLevel= 4
UNET DZMax Abort= 100
UNET Convert EG Bridges= 0
UNET Use Existing IB Tables=-1
UNET Froude Reduction=False
UNET Froude Limit= 1
UNET Froude Power= 10
UNET Time Slicing=0,0, 5
UNET Junction Losses=0
Instantaneous Interval=1HOUR
Write IC File= 0
Write IC File at Sim End=0
Echo Input=False
Echo Parameters=False
Echo Output=False
Write Detailed= 0
WQ AD Non Conservative
WQ ULTIMATE=-1
WQ Max Comp Step=1HOUR
WQ Output Interval=15MIN
WQ Output Selected Increments= 0
WQ Output face flow=0
WQ Output face velocity=0
WQ Output face area=0
WQ Output face dispersion=0
WQ Output cell volume=0
WQ Output cell surface area=0
WQ Output cell continuity=0
WQ Output cumulative cell continuity=0
WQ Output face conc=0
WQ Output face dconc_dx=0
WQ Output face courant=0
WQ Output face peclet=0
WQ Output face adv mass=0
WQ Output face disp mass=0
WQ Output cell mass=0
WQ Output cell source sink temp=0
WQ Output cell source sink nsm=0
WQ Output MaxMinRange=-1
WQ Daily Max Min Mean=-1
WQ Daily Range=0
WQ Daily Time=0
WQ Create Restart=0
WQ Fixed Restart=0
WQ System Summary=0
WQ Use Fixed Temperature=0
Sorting and Armoring Iterations= 10
XS Update Threshold= 0.02
Hydraulics Update Threshold= 0.02
Energy Slope Method= 1
Volume Change Method= 0
XS Weighting Method= 0
Number of US Weighted Cross Sections= 1
Number of DS Weighted Cross Sections= 1
Upstream XS Weight=0.25
Main XS Weight=0.5
Downstream XS Weight=0.25
Number of DS XS's Weighted with US Boundary= 1
Upstream Boundary Weight= 1
Weight of XSs Associated with US Boundary= 0
Number of US XS's Weighted with DS Boundary= 1
Downstream Boundary Weight= 0.5
Weight of XSs Associated with DS Boundary= 0.5
Sediment Output Level= 4
Mass or Volume Output= 0
Output Increment Type= 1
Profile and TS Output Increment= 10
XS Output Flag= 0
XS Output Increment= 10
Disregard all LS=0
Disregard all Conn=0
Disregard all Breaches=0
Disregard all Pumps=0

--- Elm 85.f01 (steady flow) ---

Flow Title=Multiple
Number of Profiles=7
Profile Names=10-year,25-year,50-year,1pct_min,100-year,1pct_plu,500-year
River Rch & RM= Elm 85,Reach-1,31915
     309     438     547     425     681     937    1070
River Rch & RM= Elm 85,Reach-1,31194
     440     635     803     630    1010    1390    1620
River Rch & RM= Elm 85,Reach-1,26242
     611     897    1150     909    1460    2010    2380
River Rch & RM= Elm 85,Reach-1,23794
     676     996    1280    1010    1630    2240    2670
River Rch & RM= Elm 85,Reach-1,20595
     896    1340    1730    1380    2210    3040    3680
River Rch & RM= Elm 85,Reach-1,14738
     936    1390    1800    1440    2310    3170    3830
River Rch & RM= Elm 85,Reach-1,9932
    1220    1830    2390    1920    3080    4230    5180
River Rch & RM= Elm 85,Reach-1,5577
    1240    1870    2430    1950    3130    4300    5250
Boundary for River Rch & Prof#=Elm 85,Reach-1,1
Up Type=0
Dn Type=3
Dn Slope=0.005
Boundary for River Rch & Prof#=Elm 85,Reach-1,2
Up Type=0
Dn Type=3
Dn Slope=0.005
Boundary for River Rch & Prof#=Elm 85,Reach-1,3
Up Type=0
Dn Type=3
Dn Slope=0.005
Boundary for River Rch & Prof#=Elm 85,Reach-1,4
Up Type=0
Dn Type=3
Dn Slope=0.005
Boundary for River Rch & Prof#=Elm 85,Reach-1,5
Up Type=0
Dn Type=3
Dn Slope=0.005
Boundary for River Rch & Prof#=Elm 85,Reach-1,6
Up Type=0
Dn Type=3
Dn Slope=0.005
Boundary for River Rch & Prof#=Elm 85,Reach-1,7
Up Type=0
Dn Type=3
Dn Slope=0.005

--- Elm 85.g01 (geometry) ---

Geom Title=Existing Conditions
Program Version=4.10

River Reach=Elm 85          ,Reach-1
Reach XY= 30
        1524405.        6792888.      1525151.59      6792195.77
      1526257.43      6792332.48      1527160.94      6791390.26
      1528625.52      6791668.92      1528610.09       6791185.7
      1529199.83      6790932.62      1529260.52      6790385.57
      1530551.39       6788636.5        1530605.        6787138.
      1530206.58      6786444.05      1530463.11      6785431.93
      1531001.55      6784986.51      1530957.23      6784143.93
       1531547.7      6783087.92      1531406.49      6782199.49
      1532204.46      6780077.31       1532153.5      6779049.43
      1531813.28      6779084.94        1531705.        6778738.
       1532041.2      6778051.36      1532649.64      6777990.77
      1533008.39       6776039.4      1533549.55      6775840.47
      1533413.05      6775284.71      1534004.91      6773772.61
      1533708.46       6772989.5      1534750.41      6772532.83
      1534608.37      6772089.22        1535005.        6771888.

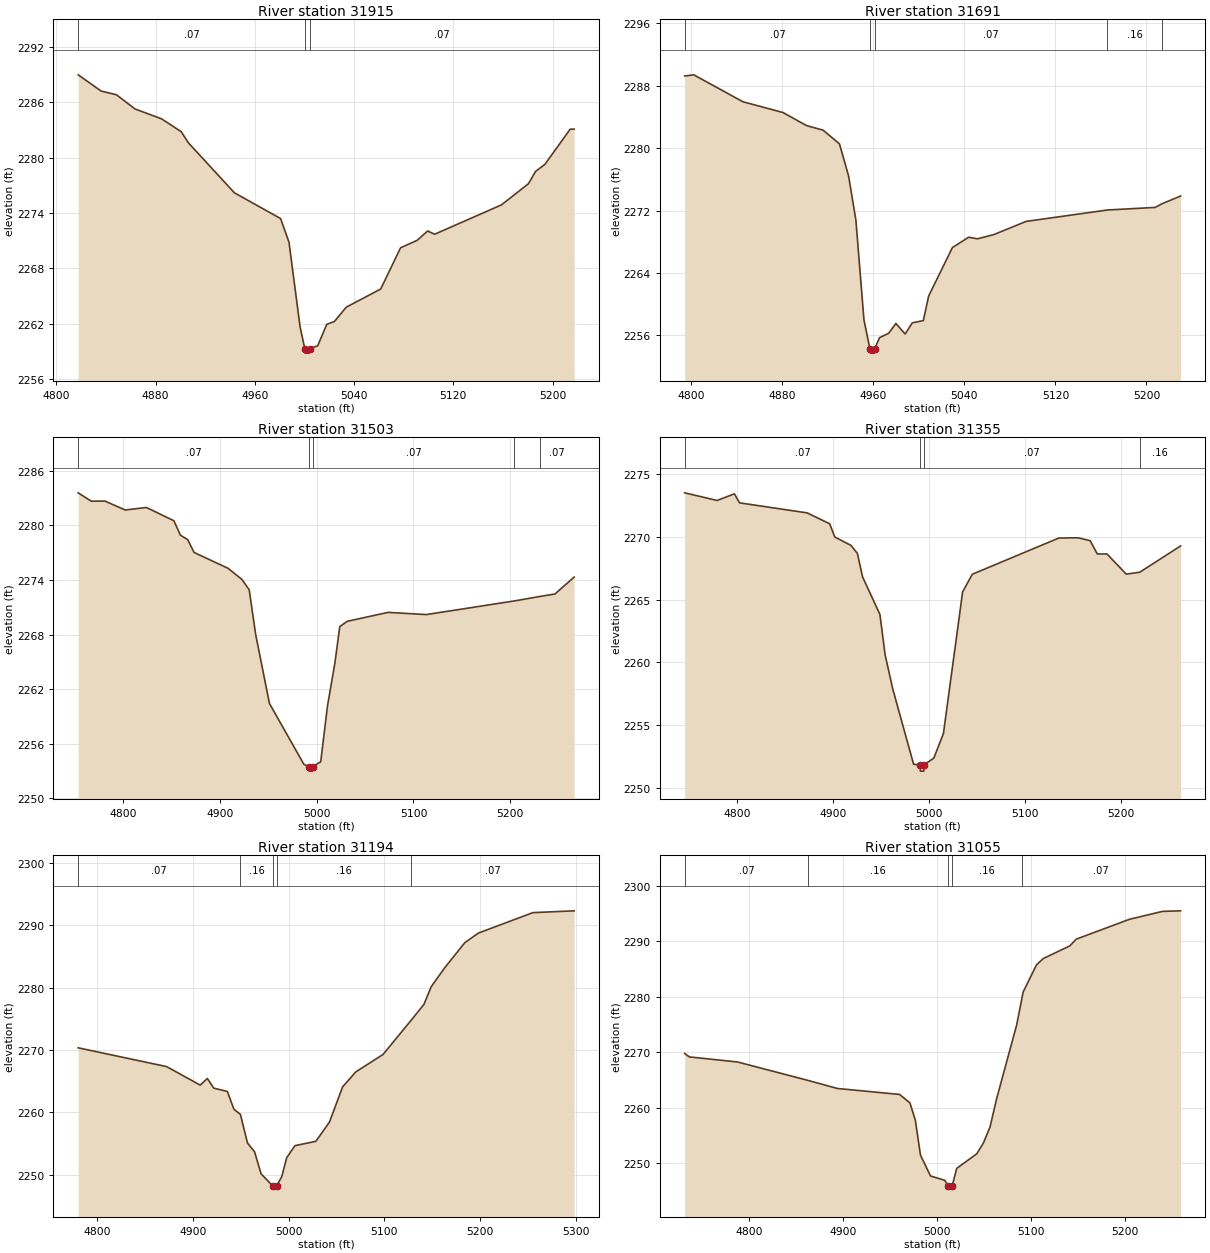
Type RM Length L Ch R = 1 ,31915   ,224,224,224
BEGIN DESCRIPTION:
15
END DESCRIPTION:
XS GIS Cut Line= 3
      1524531.97      6793044.56      1524429.57      6792869.77
      1524334.05      6792697.34
#Sta/Elev= 30
  4817.7 2288.98  4836.2 2287.22  4848.5 2286.82  4863.5 2285.28    4885  2284.2
  4900.7 2282.82  4906.5 2281.61  4943.6 2276.19  4980.8  2273.4  4987.6 2270.83
  4996.5 2261.67  5000.3 2259.31  5000.5 2258.81    5004 2258.81  5004.3 2259.31
  5010.7  2259.6    5018 2261.93  5024.2 2262.24  5033.7 2263.79  5061.5 2265.76
  5077.5 2270.23  5090.9 2271.04  5099.3 2272.05    5105  2271.7  5158.8 2274.88
  5180.6 2277.18  5186.3 2278.51  5193.8 2279.27  5214.2 2283.09  5217.4 2283.09
#Mann= 3 ,-1 , 0
  4817.7     .07       0  5000.3     .07       0  5004.3     .07       0
Bank Sta=5000.3,5004.3
XS Rating Curve= 0 ,0
Exp/Cntr=0.3,0.1

Type RM Length L Ch R = 1 ,31691   ,188,188,188
BEGIN DESCRIPTION:
741
END DESCRIPTION:
XS GIS Cut Line= 3
      1524733.33      6792921.26      1524605.06       6792760.2
      1524457.14      6792583.94
#Sta/Elev= 30
  4794.1 2289.25  4802.1  2289.4  4845.3 2285.95  4880.5 2284.57  4901.3 2282.89
  4915.8 2282.31  4930.2 2280.55  4938.2 2276.44  4944.6 2270.82  4951.7 2258.02
    4957 2254.24  4957.3 2253.74  4960.8 2253.74    4961 2254.24  4965.4 2255.72
  4973.4 2256.28  4979.8 2257.54  4987.9 2256.19  4994.2 2257.62  5003.9 2257.91
  5008.6 2261.06  5029.5 2267.27  5043.8 2268.59  5051.6 2268.39  5065.9 2268.93
  5094.3 2270.62  5165.8 2272.08  5207.7 2272.41  5213.9 2272.89  5230.1 2273.87
#Mann= 5 ,-1 , 0
  4794.1     .07       0    4957     .07       0    4961     .07       0
  5165.8     .16       0  5213.9     .07       0
Bank Sta=4957,4961
XS Rating Curve= 0 ,0
Exp/Cntr=0.3,0.1

Type RM Length L Ch R = 1 ,31503   ,148,148,148
BEGIN DESCRIPTION:
740
END DESCRIPTION:
XS GIS Cut Line= 3
       1524910.7      6792781.43      1524721.91       6792616.5
      1524465.49      6792562.63
#Sta/Elev= 30
  4753.4 2283.59  4766.9 2282.67  4781.1 2282.68    4802  2281.7  4823.9 2281.98
  4852.3 2280.52    4859 2278.94  4866.6 2278.44  4873.2 2277.03  4908.3 2275.29
  4922.6 2274.07  4930.2 2272.92  4936.8 2268.04  4951.1 2260.42  4986.7 2253.73
  4991.8 2253.48    4992 2252.98  4995.5 2252.98  4995.8 2253.48  5004.1 2254.01
  5011.1 2260.15  5018.7 2264.83  5023.8 2268.88  5031.6 2269.46  5073.7 2270.44
  5113.3  2270.2  5204.4  2271.7  5230.6 2272.19  5246.2 2272.46  5266.1 2274.32
#Mann= 5 ,-1 , 0
  4753.4     .07       0  4991.8     .07       0  4995.8     .07       0
  5204.4     .16       0  5230.6     .07       0
Bank Sta=4991.8,4995.8
XS Rating Curve= 0 ,0
Exp/Cntr=0.3,0.1

Type RM Length L Ch R = 1 ,31355   ,161,161,161
BEGIN DESCRIPTION:
739
END DESCRIPTION:
XS GIS Cut Line= 3
      1525053.91      6792625.17       1524823.9      6792525.36
      1524558.45      6792505.93
#Sta/Elev= 30
  4745.2 2273.53    4779 2272.92    4797 2273.45  4802.4 2272.73  4872.8 2271.93
  4896.3 2271.06  4901.7    2270  4918.4 2269.34  4925.2  2268.7  4930.6 2266.82
  4948.7 2263.82  4954.1 2260.61    4962 2257.89  4983.8 2251.86  4990.6 2251.81
  4990.9 2251.31  4994.4 2251.31  4994.6 2251.81  5004.9 2252.35  5014.9 2254.32
  5034.9 2265.62    5045 2267.03  5135.2 2269.92  5155.3 2269.94  5167.8 2269.71
  5175.3 2268.65  5185.3 2268.65  5205.4 2267.04  5219.5 2267.19  5262.1 2269.29
#Mann= 4 ,-1 , 0
  4745.2     .07       0  4990.6     .07       0  4994.6     .07       0
  5219.5     .16       0
Bank Sta=4990.6,4994.6
XS Rating Curve= 0 ,0
Exp/Cntr=0.3,0.1

Type RM Length L Ch R = 1 ,31194   ,139,139,139
BEGIN DESCRIPTION:
738
END DESCRIPTION:
XS GIS Cut Line= 3
      1525095.17      6792557.91      1524932.41      6792410.34
      1524734.91      6792186.79
#Sta/Elev= 30
  4780.2 2270.36  4872.5 2267.35  4907.6 2264.38  4915.1 2265.44  4921.8 2263.89
    4936 2263.36  4942.8 2260.51  4949.6 2259.68    4957 2255.09  4964.4 2253.67
  4971.2 2250.14  4983.4 2248.18  4983.6 2247.68  4987.4 2248.18  4992.8 2249.69
  4997.9  2252.7  5006.6 2254.66  5028.4 2255.35  5042.6 2258.43  5056.4 2264.11
  5070.2  2266.5  5098.6  2269.3  5127.6 2274.72  5141.3 2277.33  5148.9 2280.17
  5163.1 2283.23    5184 2287.24  5198.2 2288.78  5255.1 2292.06  5298.2 2292.35
#Mann= 5 ,-1 , 0
  4780.2     .07       0  4949.6     .16       0  4983.4     .07       0
  4987.4     .16       0  5127.6     .07       0
Bank Sta=4983.4,4987.4
XS Rating Curve= 0 ,0
Exp/Cntr=0.3,0.1

Type RM Length L Ch R = 1 ,31055   ,116,116,116
BEGIN DESCRIPTION:
737
END DESCRIPTION:
XS GIS Cut Line= 3
      1525142.92      6792555.76       1525027.9      6792306.17
      1524852.09      6792123.85
#Sta/Elev= 30
  4731.4 2269.77  4736.4 2269.15  4787.8 2268.23  4862.9  2264.9  4894.1 2263.45
  4960.2 2262.38  4971.2 2260.86    4977 2257.76  4982.5 2251.42  4993.2 2247.66
  5008.4 2246.88  5012.1 2245.79  5012.4 2245.29  5015.9 2245.29  5016.1 2245.79
  5021.1 2249.04  5042.4 2251.66  5049.4 2253.58  5056.6 2256.53  5063.5 2261.55
  5084.9  2274.9  5090.4 2279.64  5091.8 2280.85    5106 2285.75  5113.2  2286.9
  5141.5 2289.18  5148.4  2290.4    5205 2293.98  5240.2 2295.41  5259.5 2295.51
#Mann= 5 ,-1 , 0
  4731.4     .07       0  4862.9     .16       0  5012.1     .07       0
  5016.1     .16       0  5090.4     .07       0
Bank Sta=5012.1,5016.1
XS Rating Curve= 0 ,0
Exp/Cntr=0.3,0.1

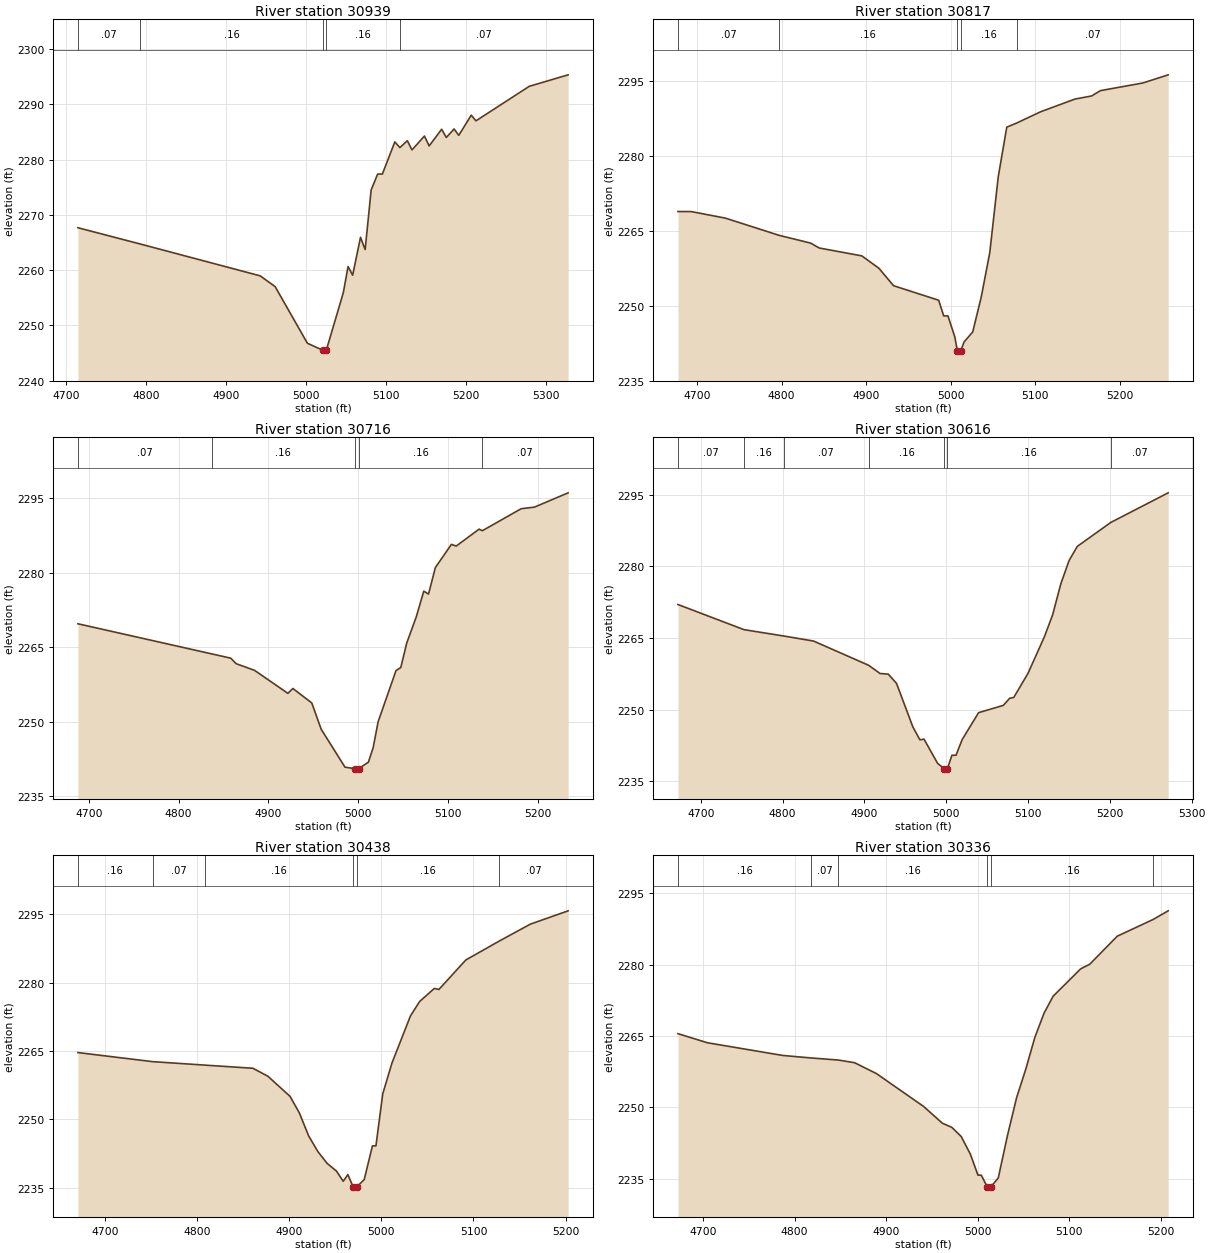
Type RM Length L Ch R = 1 ,30939   ,122,122,122
BEGIN DESCRIPTION:
736
END DESCRIPTION:
XS GIS Cut Line= 3
      1525149.43      6792512.35      1525110.36       6792217.2
      1524949.91      6791946.16
#Sta/Elev= 30
  4715.2 2267.67  4792.7 2264.74    4943 2258.96  4961.7 2257.01    5002 2246.76
  5021.6 2245.47  5021.9 2244.97  5025.6 2245.47  5046.9 2255.91  5052.8 2260.64
  5058.6 2259.08  5068.4 2265.94  5074.2 2263.72  5081.7  2274.5  5089.8 2277.38
  5095.7 2277.38  5111.3 2283.22  5117.6 2282.18  5126.9 2283.42  5132.7 2281.76
  5148.3 2284.27  5154.2 2282.48  5169.8  2285.5  5175.6 2284.01  5185.4 2285.55
  5191.2 2284.39  5206.8 2288.05  5212.7 2287.02  5279.3 2293.27  5327.9 2295.35
#Mann= 5 ,-1 , 0
  4715.2     .07       0  4792.7     .16       0  5021.6     .07       0
  5025.6     .16       0  5117.6     .07       0
Bank Sta=5021.6,5025.6
XS Rating Curve= 0 ,0
Exp/Cntr=0.3,0.1

Type RM Length L Ch R = 1 ,30817   ,101,101,101
BEGIN DESCRIPTION:
735
END DESCRIPTION:
XS GIS Cut Line= 3
      1525164.62      6792553.55      1525208.02      6792241.07
      1525240.57      6791978.46
#Sta/Elev= 30
  4677.3 2268.85    4693 2268.84  4733.4 2267.53  4797.1 2264.08  4834.3 2262.53
  4844.4 2261.55  4894.9 2259.97  4915.1 2257.49  4932.4    2254  4985.8 2251.09
  4991.8 2247.95  4996.8 2247.95  5004.9 2243.75  5007.9    2241  5008.2  2240.5
  5011.7  2240.5    5012    2241    5016 2242.77  5026.1 2244.74  5036.2 2251.74
  5046.3 2260.64  5056.3 2275.79  5066.4 2285.74    5078 2286.56  5106.7 2288.84
    5147 2291.36  5166.8 2291.99  5177.3 2293.06  5227.6 2294.59  5257.4 2296.22
#Mann= 5 ,-1 , 0
  4677.3     .07       0  4797.1     .16       0  5007.9     .07       0
    5012     .16       0    5078     .07       0
Bank Sta=5007.9,5012
XS Rating Curve= 0 ,0
Exp/Cntr=0.3,0.1

Type RM Length L Ch R = 1 ,30716   ,100,100,100
BEGIN DESCRIPTION:
734
END DESCRIPTION:
XS GIS Cut Line= 3
      1525197.15      6792575.32      1525294.82      6792277.96
      1525372.96      6792058.76
#Sta/Elev= 30
  4687.9 2269.75  4836.8 2263.69    4858 2262.83    4864 2261.72  4884.5 2260.38
  4921.6 2255.75  4927.2 2256.72  4948.2 2253.82  4958.7 2248.52  4985.2 2240.89
  4996.2 2240.59  4996.4 2240.09  5000.3 2240.59  5011.2 2241.88  5016.5 2244.77
  5022.1 2250.04    5042 2260.34  5047.3 2260.94  5053.9 2265.86  5064.5 2271.12
  5072.9 2276.32  5078.2 2275.73  5085.8 2281.07  5103.7 2285.74    5109 2285.39
  5134.5  2288.8  5138.1 2288.48  5181.3 2292.91  5196.1 2293.23  5233.6 2296.11
#Mann= 5 ,-1 , 0
  4687.9     .07       0  4836.8     .16       0  4996.2     .07       0
  5000.3     .16       0  5138.1     .07       0
Bank Sta=4996.2,5000.3
XS Rating Curve= 0 ,0
Exp/Cntr=0.3,0.1

Type RM Length L Ch R = 1 ,30616   ,178,178,178
BEGIN DESCRIPTION:
733
END DESCRIPTION:
XS GIS Cut Line= 3
      1525346.91      6792664.27      1525372.95      6792327.88
      1525398.99      6792067.47
#Sta/Elev= 30
  4672.2 2271.99  4752.9 2266.73  4801.5  2265.4  4837.9 2264.35  4905.3 2259.27
  4919.2 2257.56  4929.2 2257.43  4939.3 2255.49  4959.3 2246.38  4967.9 2243.69
  4972.9 2243.83  4989.4  2238.8  4997.4 2237.64  4997.6 2237.14  5001.5 2237.64
    5007 2240.46    5012 2240.46  5019.5 2243.73  5039.6 2249.37  5069.8 2250.89
  5077.6 2252.38  5082.6 2252.56  5099.9 2257.56    5120 2265.23  5130.1 2269.83
  5140.1 2276.31  5150.2 2281.19  5160.2 2284.14  5201.2 2289.16  5271.3 2295.35
#Mann= 7 ,-1 , 0
  4672.2     .07       0  4752.9     .16       0  4801.5     .07       0
  4905.3     .16       0  4997.4     .07       0  5001.5     .16       0
  5201.2     .07       0
Bank Sta=4997.4,5001.5
XS Rating Curve= 0 ,0
Exp/Cntr=0.3,0.1

Type RM Length L Ch R = 1 ,30438   ,102,102,102
BEGIN DESCRIPTION:
732
END DESCRIPTION:
XS GIS Cut Line= 3
      1525474.94      6792566.64      1525514.01      6792245.41
      1525500.99      6792037.11
#Sta/Elev= 30
  4670.5 2264.65  4751.6 2262.66  4808.3  2261.9  4860.5 2261.21  4876.8 2259.46
  4900.8 2255.05  4910.9 2251.44    4921 2246.39    4931 2242.95  4941.1 2240.34
  4951.2 2238.67  4958.6 2236.42  4963.6 2237.89  4969.3  2235.2  4969.5  2234.7
  4973.1  2234.7  4973.4  2235.2  4981.4 2236.81  4990.3 2244.19  4994.1 2244.19
  5001.5  2255.6  5011.5 2262.36  5031.6 2272.69  5041.6 2275.87  5057.5 2278.71
  5062.5  2278.5  5091.7 2284.96  5128.1 2289.12  5161.8 2292.82  5202.8 2295.74
#Mann= 6 ,-1 , 0
  4670.5     .16       0  4751.6     .07       0  4808.3     .16       0
  4969.3     .07       0  4973.4     .16       0  5128.1     .07       0
Bank Sta=4969.3,4973.4
XS Rating Curve= 0 ,0
Exp/Cntr=0.3,0.1

Type RM Length L Ch R = 1 ,30336   ,145,145,145
BEGIN DESCRIPTION:
731
END DESCRIPTION:
XS GIS Cut Line= 3
      1525524.86      6792599.15      1525600.81      6792280.13
      1525607.31      6792072.37
#Sta/Elev= 30
  4672.5 2265.49  4704.5 2263.59  4786.8 2260.92  4817.9 2260.39  4847.8 2259.95
  4865.6 2259.39  4889.5  2257.1  4940.9 2250.22  4961.5 2246.69  4971.8 2245.82
  4982.1 2243.89  4992.1 2240.19  5000.4 2235.78    5004 2235.78  5010.5 2233.35
  5010.8 2232.85  5014.4 2232.85  5014.6 2233.35  5022.6  2235.2  5032.6 2244.06
  5042.6 2252.03  5052.6    2258  5062.6 2264.72  5072.6 2269.78  5082.6 2273.36
  5112.6 2279.09  5122.6 2280.07  5152.6 2285.95  5191.8 2289.46  5208.3 2291.28
#Mann= 6 ,-1 , 0
  4672.5     .16       0  4817.9     .07       0  4847.8     .16       0
  5010.5     .07       0  5014.6     .16       0  5191.8     .07       0
Bank Sta=5010.5,5014.6
XS Rating Curve= 0 ,0
Exp/Cntr=0.3,0.1

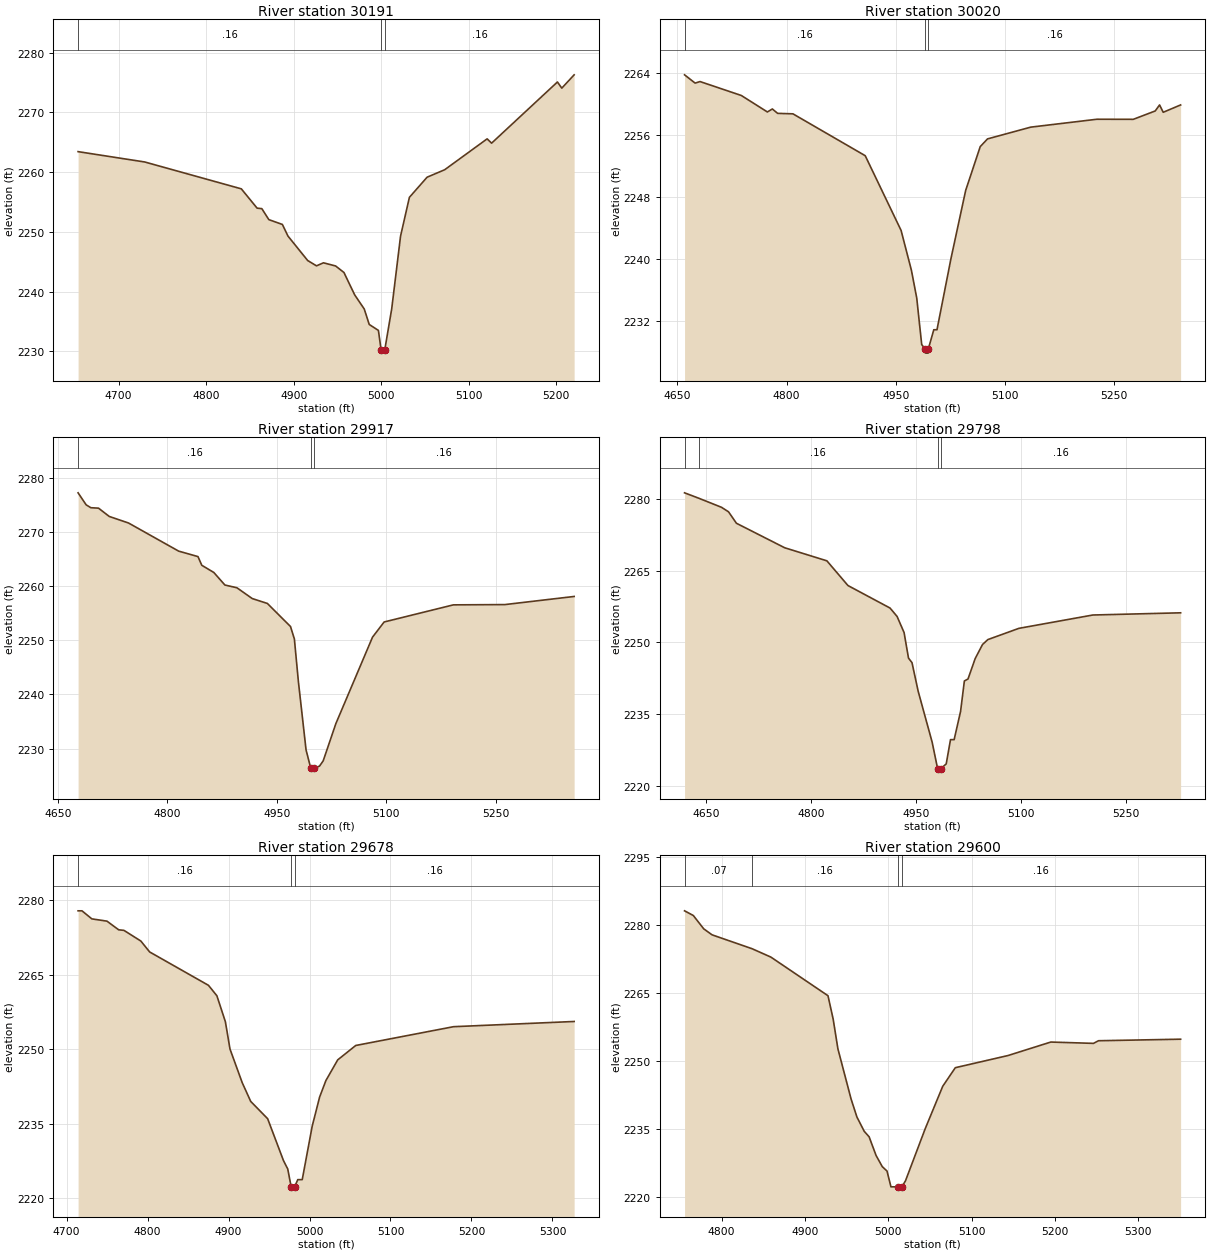
Type RM Length L Ch R = 1 ,30191   ,171,171,171
BEGIN DESCRIPTION:
730
END DESCRIPTION:
XS GIS Cut Line= 3
      1525607.33      6792607.81      1525744.04      6792293.15
      1525772.05      6792071.28
#Sta/Elev= 30
  4653.7 2263.42  4729.8 2261.69  4840.2 2257.19  4858.2 2253.96  4863.6 2253.88
  4871.6 2252.04  4887.1 2251.23  4893.4  2249.3    4916 2245.19  4926.1  2244.3
    4934 2244.81  4947.9 2244.28  4957.4 2243.19  4969.7 2239.44  4980.6 2237.08
  4986.3 2234.49  4996.8 2233.49  4999.9 2230.19  5000.2 2229.69    5004 2230.19
    5012 2237.12  5022.1 2249.29  5032.2 2255.77  5052.4 2259.14  5072.5 2260.39
    5121 2265.56  5126.1 2264.84  5201.3 2275.08  5206.3 2274.05  5220.4 2276.28
#Mann= 3 ,-1 , 0
  4653.7     .16       0  4999.9     .07       0    5004     .16       0
Bank Sta=4999.9,5004
XS Rating Curve= 0 ,0
Exp/Cntr=0.3,0.1

Type RM Length L Ch R = 1 ,30020   ,103,103,103
BEGIN DESCRIPTION:
729
END DESCRIPTION:
XS GIS Cut Line= 3
      1525620.38      6792633.83      1525872.08      6792401.66
      1525891.61      6792063.15
#Sta/Elev= 30
  4659.9  2263.8  4674.4 2262.73  4681.2 2262.93  4737.9 2261.13  4773.7    2259
  4780.5 2259.39  4787.8 2258.82  4808.8 2258.76  4908.1 2253.35  4957.4 2243.69
  4971.6 2238.53  4978.9 2234.95  4985.7 2228.95  4990.6 2228.34  4990.9 2227.84
  4994.5 2227.84  4994.7 2228.34  5002.3 2230.86  5006.7 2230.86    5026  2240.1
  5046.1 2248.86  5066.1 2254.52  5076.1 2255.52  5135.5 2257.04  5226.4 2258.06
  5276.4 2258.05  5306.5 2259.13  5312.5 2259.91  5317.5 2258.96  5341.4 2259.91
#Mann= 3 ,-1 , 0
  4659.9     .16       0  4990.6     .07       0  4994.7     .16       0
Bank Sta=4990.6,4994.7
XS Rating Curve= 0 ,0
Exp/Cntr=0.3,0.1

Type RM Length L Ch R = 1 ,29917   ,119,119,119
BEGIN DESCRIPTION:
728
END DESCRIPTION:
XS GIS Cut Line= 3
      1526063.06      6792744.57      1525961.06      6792436.38
      1525919.94       6792083.6
#Sta/Elev= 30
  4677.5 2277.21  4688.5    2275    4695 2274.46  4705.5 2274.38  4720.2 2272.85
  4746.6 2271.64  4815.3 2266.45  4841.8 2265.44    4847 2263.84  4863.5 2262.51
  4878.7 2260.19  4895.1 2259.69  4916.2 2257.69  4936.9 2256.79  4968.6 2252.53
  4973.9 2250.24  4979.4 2242.38  4989.9 2229.77  4996.4 2226.34  4996.7 2225.84
  5000.6 2225.84  5000.9 2226.34  5008.4 2226.77  5013.4 2227.74  5030.7 2234.59
    5081 2250.57  5096.9 2253.37  5191.8 2256.53  5262.3 2256.58  5357.3 2258.08
#Mann= 3 ,-1 , 0
  4677.5     .16       0  4996.4     .07       0  5000.9     .16       0
Bank Sta=4996.4,5000.9
XS Rating Curve= 0 ,0
Exp/Cntr=0.3,0.1

Type RM Length L Ch R = 1 ,29798   ,120,120,120
BEGIN DESCRIPTION:
727
END DESCRIPTION:
XS GIS Cut Line= 3
      1526095.61      6792770.61      1526065.22      6792390.81
      1525974.08      6792076.16
#Sta/Elev= 30
  4619.5 2281.28  4639.6 2280.16  4672.3 2278.25  4682.3 2277.31  4693.6 2274.91
  4762.6 2269.78  4822.8 2267.05  4852.9 2261.88    4913 2257.17  4923.1 2255.41
  4933.1 2252.03  4939.4 2246.69  4944.4 2245.74  4953.2 2239.76  4973.2 2229.09
    4981 2223.54  4981.3 2223.04  4985.5 2223.54  4993.3 2224.56  4999.4 2229.63
  5004.6 2229.63  5013.8 2235.55  5019.2 2241.91  5024.4 2242.32  5034.7 2246.61
  5045.1 2249.53  5052.8 2250.57  5097.1 2252.92  5202.7 2255.71  5328.1 2256.17
#Mann= 4 ,-1 , 0
  4619.5     .07       0  4639.6     .16       0    4981     .07       0
  4985.5     .16       0
Bank Sta=4981,4985.5
XS Rating Curve= 0 ,0
Exp/Cntr=0.3,0.1

Type RM Length L Ch R = 1 ,29678   ,78,78,78
BEGIN DESCRIPTION:
725
END DESCRIPTION:
XS GIS Cut Line= 3
      1526254.03      6792612.18       1526175.9      6792351.75
      1526026.15      6792045.73
#Sta/Elev= 30
  4714.2 2277.83    4719 2277.83  4731.2 2276.21  4749.9 2275.75  4764.3 2274.01
  4770.8  2273.9  4791.7 2271.75  4802.6 2269.55  4875.2 2262.84  4885.6 2260.74
  4896.1 2255.51  4901.8 2250.01  4916.9 2243.24  4927.4 2239.47  4948.3 2235.99
  4967.9 2227.54  4973.1 2225.88  4977.3 2222.32  4977.6 2221.82  4981.5 2221.82
  4981.8 2222.32  4985.5 2223.73    4991 2223.73  5003.3 2234.48  5012.5 2240.36
  5020.2 2243.66  5034.8 2247.83  5057.1 2250.73  5177.8 2254.51  5326.8 2255.56
#Mann= 3 ,-1 , 0
  4714.2     .16       0  4977.3     .07       0  4981.8     .16       0
Bank Sta=4977.3,4981.8
XS Rating Curve= 0 ,0
Exp/Cntr=0.3,0.1

Type RM Length L Ch R = 1 ,29600   ,107,107,107
BEGIN DESCRIPTION:
726
END DESCRIPTION:
XS GIS Cut Line= 3
      1526369.07       6792547.1      1526245.35      6792332.22
       1526054.9      6792042.22
#Sta/Elev= 30
  4755.7 2283.13  4766.2  2282.1  4778.7 2279.16  4788.7 2277.84  4836.7 2274.78
  4859.2 2272.94  4927.7 2264.43  4933.9  2259.3  4939.6 2252.73  4955.4 2241.68
  4962.4 2237.71  4971.2 2234.55    4977 2233.36  4985.4 2229.23  4992.8 2226.78
  4998.5  2225.8  5003.2 2222.33  5011.8 2222.32  5012.1 2221.82    5016 2221.82
  5016.3 2222.32  5020.7 2223.67  5044.2 2235.08  5065.3 2244.47  5080.4 2248.57
  5143.6 2251.25  5194.9 2254.22  5246.1 2253.93  5252.1 2254.51  5350.6 2254.85
#Mann= 4 ,-1 , 0
  4755.7     .07       0  4836.7     .16       0  5011.8     .07       0
  5016.3     .16       0
Bank Sta=5011.8,5016.3
XS Rating Curve= 0 ,0
Exp/Cntr=0.3,0.1

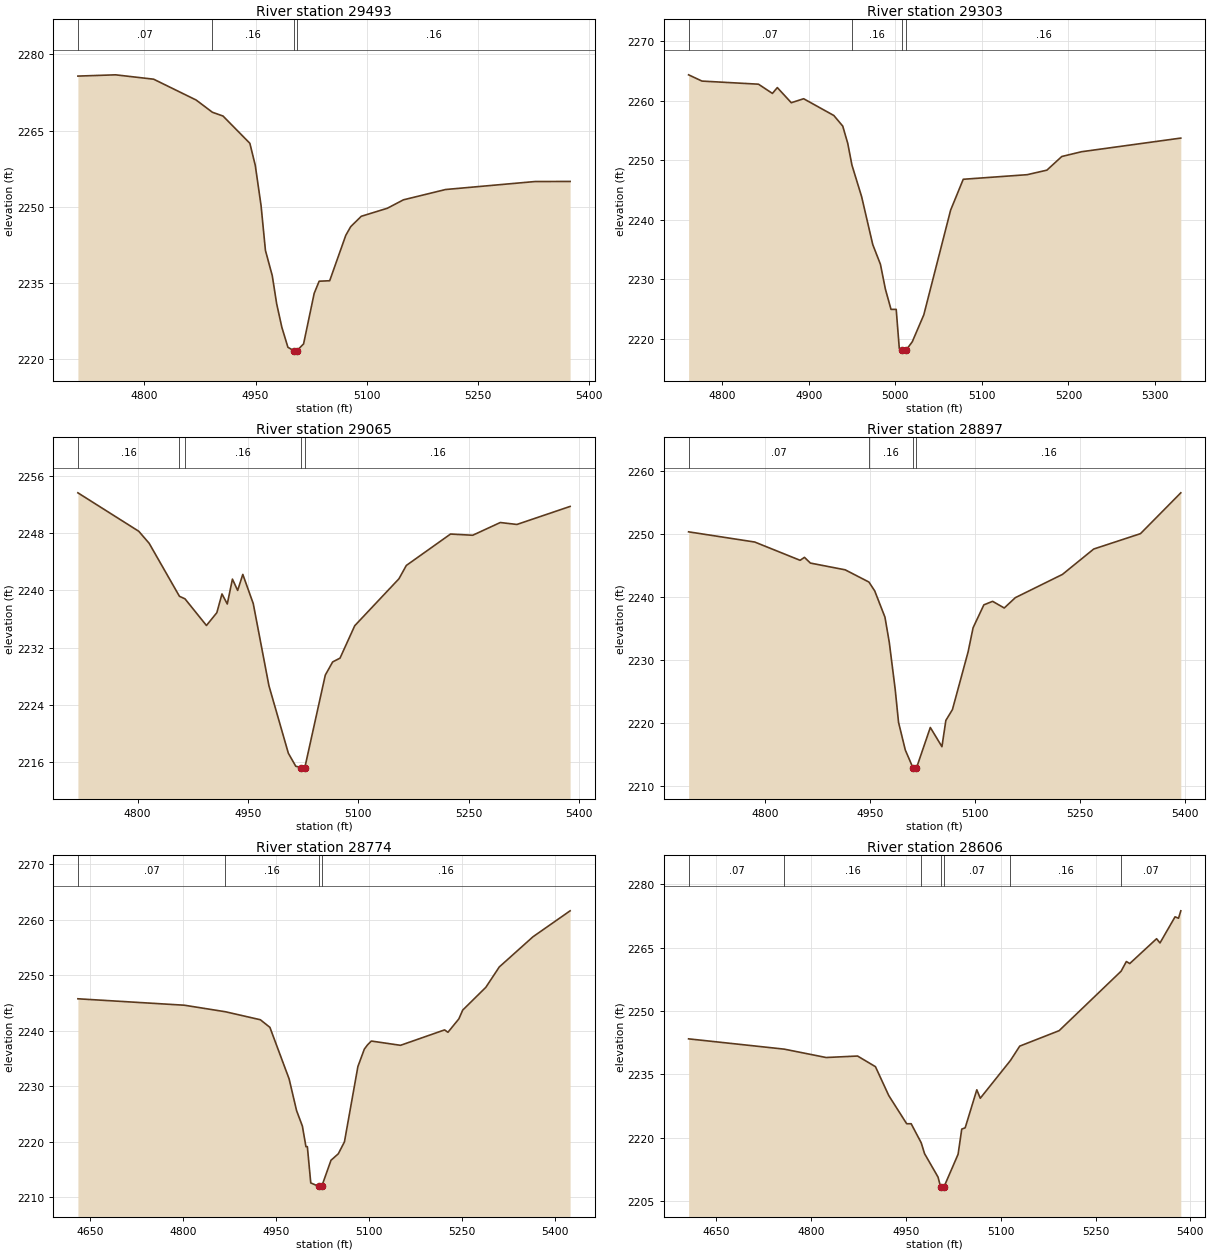
Type RM Length L Ch R = 1 ,29493   ,190,190,190
BEGIN DESCRIPTION:
724
END DESCRIPTION:
XS GIS Cut Line= 3
      1526486.24      6792508.01      1526325.64      6792262.77
      1526050.03      6792015.38
#Sta/Elev= 30
  4710.5 2275.74  4761.3 2275.99  4812.6 2275.13  4869.9 2271.03  4891.8 2268.62
  4906.1 2267.88  4942.3 2262.51  4949.6 2258.17  4957.4 2250.25  4963.3 2241.42
  4972.5 2236.45  4978.4 2230.94  4985.4  2226.3  4993.6 2222.35  5001.3  2221.7
  5001.6  2221.2  5005.5  2221.2  5005.8  2221.7  5014.7 2223.01    5029 2232.96
  5035.7 2235.36  5049.9 2235.45  5071.6 2244.39  5078.3 2246.11  5092.5 2248.14
  5127.6 2249.72  5149.3 2251.38  5206.1 2253.41  5326.5 2254.98    5374    2255
#Mann= 4 ,-1 , 0
  4710.5     .07       0  4891.8     .16       0  5001.3     .07       0
  5005.8     .16       0
Bank Sta=5001.3,5005.8
XS Rating Curve= 0 ,0
Exp/Cntr=0.3,0.1

Type RM Length L Ch R = 1 ,29303   ,238,238,238
BEGIN DESCRIPTION:
723
END DESCRIPTION:
XS GIS Cut Line= 3
      1526568.71      6792334.41      1526453.68      6792126.05
      1526154.23      6791985.01
#Sta/Elev= 30
  4760.9 2264.32  4776.4 2263.27  4841.7 2262.75  4857.8  2261.2  4863.5 2262.18
  4879.6 2259.64  4893.9 2260.31  4928.8  2257.5  4939.1 2255.72  4944.9 2252.82
  4949.7  2249.2  4960.9  2243.9  4973.8 2235.85  4982.7 2232.53  4988.4 2228.38
  4994.9 2224.98  5000.9 2224.98  5004.5  2218.4  5007.8 2218.14  5008.1 2217.64
  5012.3 2218.14  5019.5 2219.55  5032.8 2224.06  5063.8 2241.62  5078.4  2246.8
  5152.3 2247.57  5175.1 2248.33  5192.3 2250.62  5215.1 2251.42  5329.9 2253.71
#Mann= 4 ,-1 , 0
  4760.9     .07       0  4949.7     .16       0  5007.8     .07       0
  5012.3     .16       0
Bank Sta=5007.8,5012.3
XS Rating Curve= 0 ,0
Exp/Cntr=0.3,0.1

Type RM Length L Ch R = 1 ,29065   ,168,168,168
BEGIN DESCRIPTION:
722
END DESCRIPTION:
XS GIS Cut Line= 3
       1526794.4       6792145.6      1526592.57      6791939.42
      1526212.81      6791917.72
#Sta/Elev= 30
  4718.9 2253.64  4801.6 2248.27  4815.7 2246.59  4856.9 2239.18  4864.4 2238.83
  4893.6  2235.1  4907.7 2236.89  4914.7 2239.51  4921.9 2238.11  4928.9 2241.58
    4936    2240    4943 2242.24  4957.2 2238.16  4978.5 2226.69  5004.9 2217.25
    5015 2215.43  5022.7 2215.25    5023 2214.75  5027.3 2215.25  5055.1 2228.17
  5065.1 2230.01  5075.1 2230.54  5095.1 2235.07  5155.2 2241.63  5165.2 2243.49
  5225.3 2247.88  5255.4 2247.71  5292.9 2249.49  5315.5 2249.22  5387.8 2251.74
#Mann= 5 ,-1 , 0
  4718.9     .16       0  4856.9     .07       0  4864.4     .16       0
  5022.7     .07       0  5027.3     .16       0
Bank Sta=5022.7,5027.3
XS Rating Curve= 0 ,0
Exp/Cntr=0.3,0.1

Type RM Length L Ch R = 1 ,28897   ,123,123,123
BEGIN DESCRIPTION:
721
END DESCRIPTION:
XS GIS Cut Line= 3
      1526935.47      6791989.35      1526692.39      6791811.38
      1526334.29      6791629.07
#Sta/Elev= 30
  4690.4 2250.34  4784.9 2248.72  4849.7 2245.82  4855.9 2246.29  4864.4 2245.38
  4914.1 2244.31    4948 2242.37  4956.3 2240.96  4970.9  2236.8  4977.1 2232.79
  4985.6 2225.27  4990.3  2220.1    5000  2215.7    5011 2212.86  5011.4 2212.36
  5015.9 2212.86  5035.7 2219.29  5052.3 2216.24  5057.9 2220.41  5067.3 2222.13
  5089.7  2231.3  5096.8 2235.12  5112.2 2238.75  5124.7 2239.31  5141.3 2238.25
  5157.1 2239.89  5224.4 2243.58  5269.1 2247.61  5335.9 2250.05  5393.5 2256.53
#Mann= 4 ,-1 , 0
  4690.4     .07       0    4948     .16       0    5011     .07       0
  5015.9     .16       0
Bank Sta=5011,5015.9
XS Rating Curve= 0 ,0
Exp/Cntr=0.3,0.1

Type RM Length L Ch R = 1 ,28774   ,168,168,168
BEGIN DESCRIPTION:
720
END DESCRIPTION:
XS GIS Cut Line= 3
      1527056.98      6791891.68      1526740.14      6791700.71
      1526349.76      6791535.88
#Sta/Elev= 30
  4630.3 2245.74    4802 2244.58  4868.3  2243.4  4924.5 2241.96  4939.9 2240.59
  4970.9 2231.29  4982.9 2225.58  4992.3 2222.78    4998 2219.08  5000.3 2219.08
  5005.8 2212.54  5018.6 2211.92    5019 2211.42  5023.5 2211.92  5038.4 2216.62
  5050.2 2217.79  5060.1 2219.94  5081.8 2233.52  5092.2 2236.67  5097.6 2237.47
  5103.5 2238.12  5150.5 2237.35  5221.6 2240.13    5227  2239.7  5244.6 2242.12
  5250.8  2243.7  5288.1 2247.81  5309.8 2251.48    5364 2256.91    5424  2261.6
#Mann= 4 ,-1 , 0
  4630.3     .07       0  4868.3     .16       0  5018.6     .07       0
  5023.5     .16       0
Bank Sta=5018.6,5023.5
XS Rating Curve= 0 ,0
Exp/Cntr=0.3,0.1

Type RM Length L Ch R = 1 ,28606   ,147,147,147
BEGIN DESCRIPTION:
718
END DESCRIPTION:
XS GIS Cut Line= 3
      1527109.06      6791841.76      1526820.43      6791557.48
      1526677.33      6791212.72
#Sta/Elev= 30
  4606.5 2243.38  4757.9 2240.94  4824.1 2238.96  4873.7 2239.31    4902 2236.79
  4923.1 2229.94  4951.4 2223.27  4958.5 2223.27  4974.4 2218.75  4979.7 2216.18
    5001 2210.63  5005.1 2208.28  5005.5 2207.78  5010.3 2208.28  5032.7 2216.04
  5038.5    2222  5043.9  2222.3  5062.3 2231.31  5067.8 2229.31  5115.5 2238.26
  5130.2 2241.66  5192.5 2245.32  5290.5 2259.41  5298.8  2261.7  5304.2 2261.22
  5346.6  2267.1    5352  2266.1  5375.8 2272.29  5381.3 2271.95  5384.9 2273.71
#Mann= 7 ,-1 , 0
  4606.5     .07       0  4757.9     .16       0  4974.4     .07       0
  5005.1     .07       0  5010.3     .07       0  5115.5     .16       0
  5290.5     .07       0
Bank Sta=5005.1,5010.3
XS Rating Curve= 0 ,0
Exp/Cntr=0.3,0.1

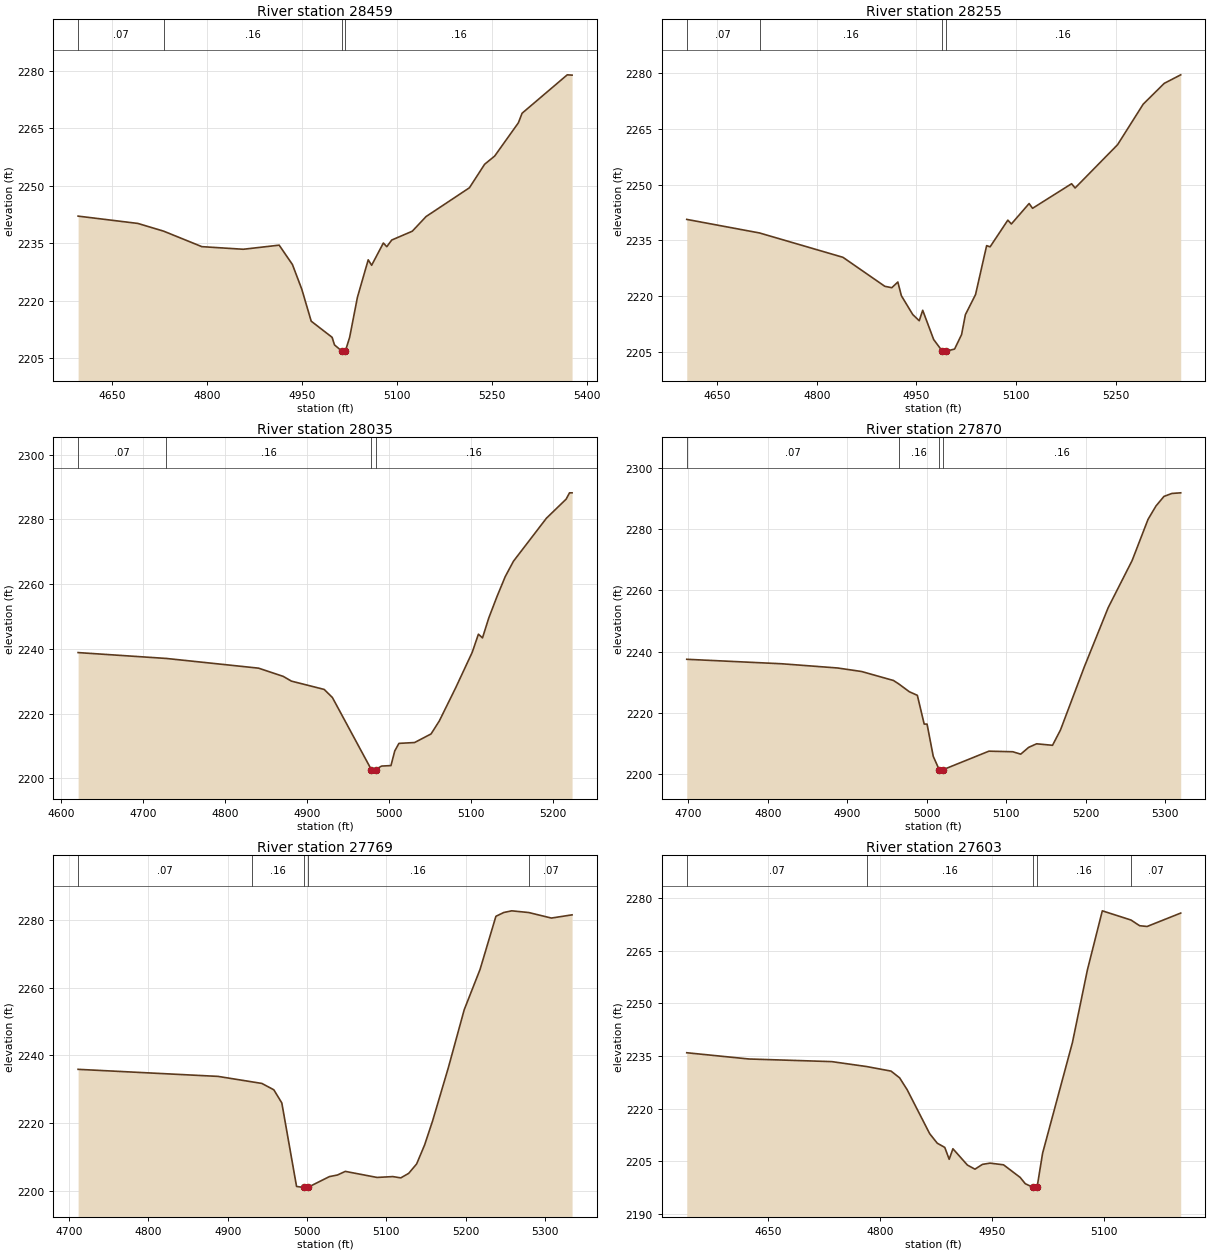
Type RM Length L Ch R = 1 ,28459   ,204,204,204
BEGIN DESCRIPTION:
719
END DESCRIPTION:
XS GIS Cut Line= 3
      1527182.84      6791822.22      1526952.81      6791496.71
      1526807.42      6791145.18
#Sta/Elev= 30
  4596.9 2242.11  4691.2  2240.2  4731.7 2238.19  4792.1 2234.14  4857.4 2233.46
    4914 2234.53  4934.9 2229.47  4949.7 2223.01  4964.5 2214.69  4997.5 2210.47
  5001.2  2208.5  5013.1 2206.85  5013.5 2206.35  5018.3 2206.85  5025.1 2210.46
  5037.4 2220.93  5054.4  2230.7  5059.8 2229.28  5078.3 2235.09  5083.7 2234.13
  5091.5 2235.87  5123.9 2238.17  5145.6 2241.99    5214 2249.51    5238 2255.65
  5253.8 2257.78  5291.2 2266.46  5297.1 2268.97  5368.3 2278.99  5375.9 2278.91
#Mann= 4 ,-1 , 0
  4596.9     .07       0  4731.7     .16       0  5013.1     .07       0
  5018.3     .16       0
Bank Sta=5013.1,5018.3
XS Rating Curve= 0 ,0
Exp/Cntr=0.3,0.1

Type RM Length L Ch R = 1 ,28255   ,220,220,220
BEGIN DESCRIPTION:
717
END DESCRIPTION:
XS GIS Cut Line= 3
      1527247.94      6791791.81      1527128.59      6791418.59
      1527020.09       6791084.4
#Sta/Elev= 30
  4604.4 2240.65  4713.9 2237.01  4839.4 2230.48  4902.4  2222.7  4912.9 2222.32
    4922 2223.85  4927.3 2220.18  4944.4 2215.13  4954.2 2213.45  4959.4 2216.27
  4975.9 2208.42    4989 2205.27  4989.4 2204.77  4994.2 2205.27  5007.4 2205.87
  5017.9 2209.75  5023.6 2215.08  5038.9 2220.48  5055.6 2233.61  5060.8 2233.29
  5087.5 2240.45  5092.8 2239.42  5119.5 2244.91  5124.7 2243.63  5183.4 2250.22
  5188.7 2249.08  5252.6 2260.69  5291.2 2271.58  5322.8 2277.15  5347.6 2279.44
#Mann= 4 ,-1 , 0
  4604.4     .07       0  4713.9     .16       0    4989     .07       0
  4994.2     .16       0
Bank Sta=4989,4994.2
XS Rating Curve= 0 ,0
Exp/Cntr=0.3,0.1

Type RM Length L Ch R = 1 ,28035   ,165,165,165
BEGIN DESCRIPTION:
716
END DESCRIPTION:
XS GIS Cut Line= 3
      1527332.59      6791767.97       1527339.1      6791390.38
      1527360.79      6791166.88
#Sta/Elev= 30
    4621 2238.86  4728.4 2237.05    4841 2234.05    4871 2231.52    4881 2230.05
    4921 2227.48    4931 2224.99  4978.4 2202.75  4978.8 2202.25  4983.2 2202.25
  4983.6 2202.75    4991 2203.81  5002.4 2203.96    5007 2208.46  5012.1 2210.82
  5031.2 2211.08  5051.3 2213.74  5061.3 2217.73  5081.4 2228.04  5101.5 2238.96
    5109 2244.54    5114  2243.4  5121.6 2249.52  5131.6 2256.13  5141.7 2262.32
  5151.7 2267.06  5191.9 2280.35    5216 2286.26  5220.1  2288.2  5223.2  2288.2
#Mann= 4 ,-1 , 0
    4621     .07       0  4728.4     .16       0  4978.4     .07       0
  4983.6     .16       0
Bank Sta=4978.4,4983.6
XS Rating Curve= 0 ,0
Exp/Cntr=0.3,0.1

Type RM Length L Ch R = 1 ,27870   ,101,101,101
BEGIN DESCRIPTION:
715
END DESCRIPTION:
XS GIS Cut Line= 3
      1527449.77      6791787.53      1527467.13      6791485.86
      1527462.79      6791166.86
#Sta/Elev= 30
  4698.2 2237.47  4817.9    2236    4888 2234.62  4918.1 2233.47  4958.2 2230.53
  4964.5 2229.47  4978.2 2226.84  4988.2 2225.68  4996.8 2216.27  5000.4 2216.27
  5008.2 2205.72  5015.6 2201.38    5016 2200.88  5020.4 2200.88  5020.8 2201.38
  5078.2 2207.41  5108.2 2207.22  5118.2 2206.43  5128.2 2208.66  5138.2 2209.82
  5158.2 2209.33  5168.2 2214.35  5198.2 2235.01  5228.2 2254.37  5258.3 2269.78
  5278.3 2283.25  5288.3 2287.63  5298.3 2290.75  5308.3 2291.73  5319.4 2291.93
#Mann= 4 ,-1 , 0
  4698.2     .07       0  4964.5     .16       0  5015.6     .07       0
  5020.8     .16       0
Bank Sta=5015.6,5020.8
XS Rating Curve= 0 ,0
Exp/Cntr=0.3,0.1

Type RM Length L Ch R = 1 ,27769   ,166,166,166
BEGIN DESCRIPTION:
714
END DESCRIPTION:
XS GIS Cut Line= 3
      1527536.58      6791763.66      1527564.79      6791485.86
      1527566.95       6791141.9
#Sta/Elev= 30
  4711.2 2235.87  4887.8 2233.78  4930.8 2232.16    4943  2231.7  4958.1 2229.82
  4968.2 2225.93  4986.8 2201.21  4995.7 2200.92  4996.1 2200.42  5000.5 2200.42
  5000.9 2200.92  5028.3 2204.13  5038.3 2204.59  5048.3 2205.67  5088.3 2203.88
  5108.3 2204.13  5118.3 2203.75  5128.3 2205.09  5138.3 2207.88  5148.3 2213.46
  5158.3 2220.52  5178.3 2236.36  5198.3  2253.5  5218.3 2265.43  5238.3 2281.16
  5248.3 2282.29  5258.3 2282.78  5279.8 2282.27  5308.3 2280.64  5334.4 2281.59
#Mann= 5 ,-1 , 0
  4711.2     .07       0  4930.8     .16       0  4995.7     .07       0
  5000.9     .16       0  5279.8     .07       0
Bank Sta=4995.7,5000.9
XS Rating Curve= 0 ,0
Exp/Cntr=0.3,0.1

Type RM Length L Ch R = 1 ,27603   ,126,126,126
BEGIN DESCRIPTION:
713
END DESCRIPTION:
XS GIS Cut Line= 3
        1527593.      6791800.52      1527653.77      6791349.14
       1527651.6      6791143.01
#Sta/Elev= 30
  4540.9 2235.93  4624.2 2234.15  4735.2  2233.4  4781.7    2232  4814.5  2230.7
    4826 2228.78  4836.1 2225.39  4866.3 2212.85  4876.4 2210.15  4886.5 2208.94
  4892.4 2205.56  4897.4 2208.56  4916.8 2203.91  4926.9 2202.74    4937 2204.11
  4947.1 2204.46  4965.2 2203.98  4987.4  2200.4  4994.4 2198.58  5004.9 2197.55
  5005.3 2197.05  5010.1 2197.55  5017.5 2207.28  5057.5 2238.87  5077.5 2259.53
  5097.5 2276.39  5135.9 2273.77  5147.5 2272.14  5157.5 2271.93  5202.5 2275.75
#Mann= 5 ,-1 , 0
  4540.9     .07       0  4781.7     .16       0  5004.9     .07       0
  5010.1     .16       0  5135.9     .07       0
Bank Sta=5004.9,5010.1
XS Rating Curve= 0 ,0
Exp/Cntr=0.3,0.1