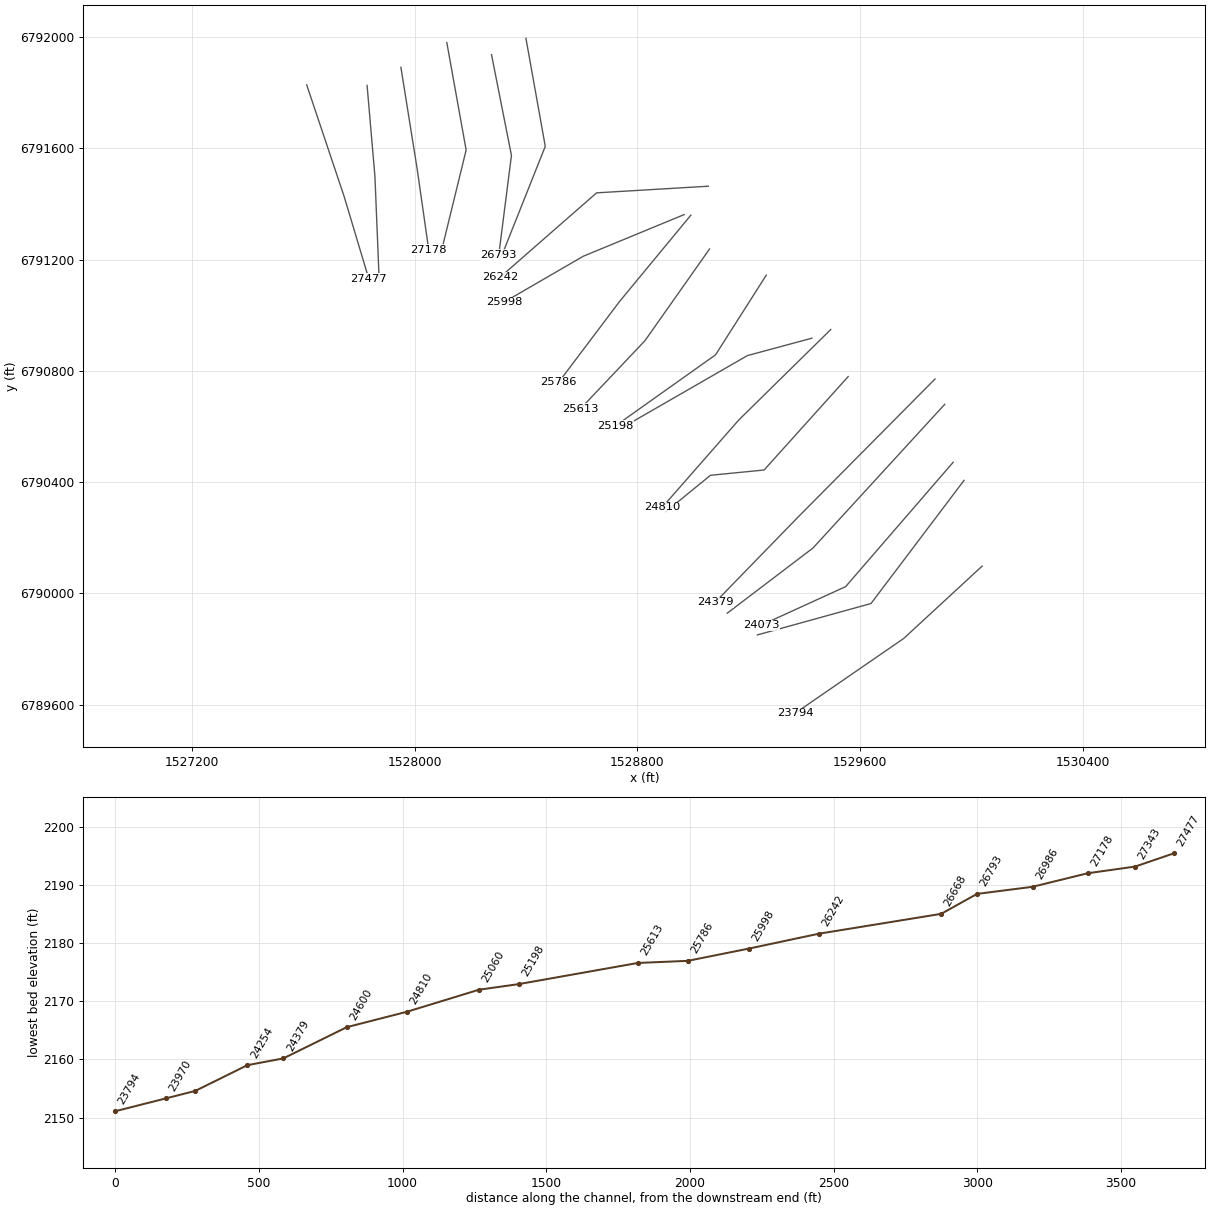
HEC-RAS study Elm 85.prj: Elm 85 Base Level Engineering

--- Elm 85.g01 (geometry) --- (continued)

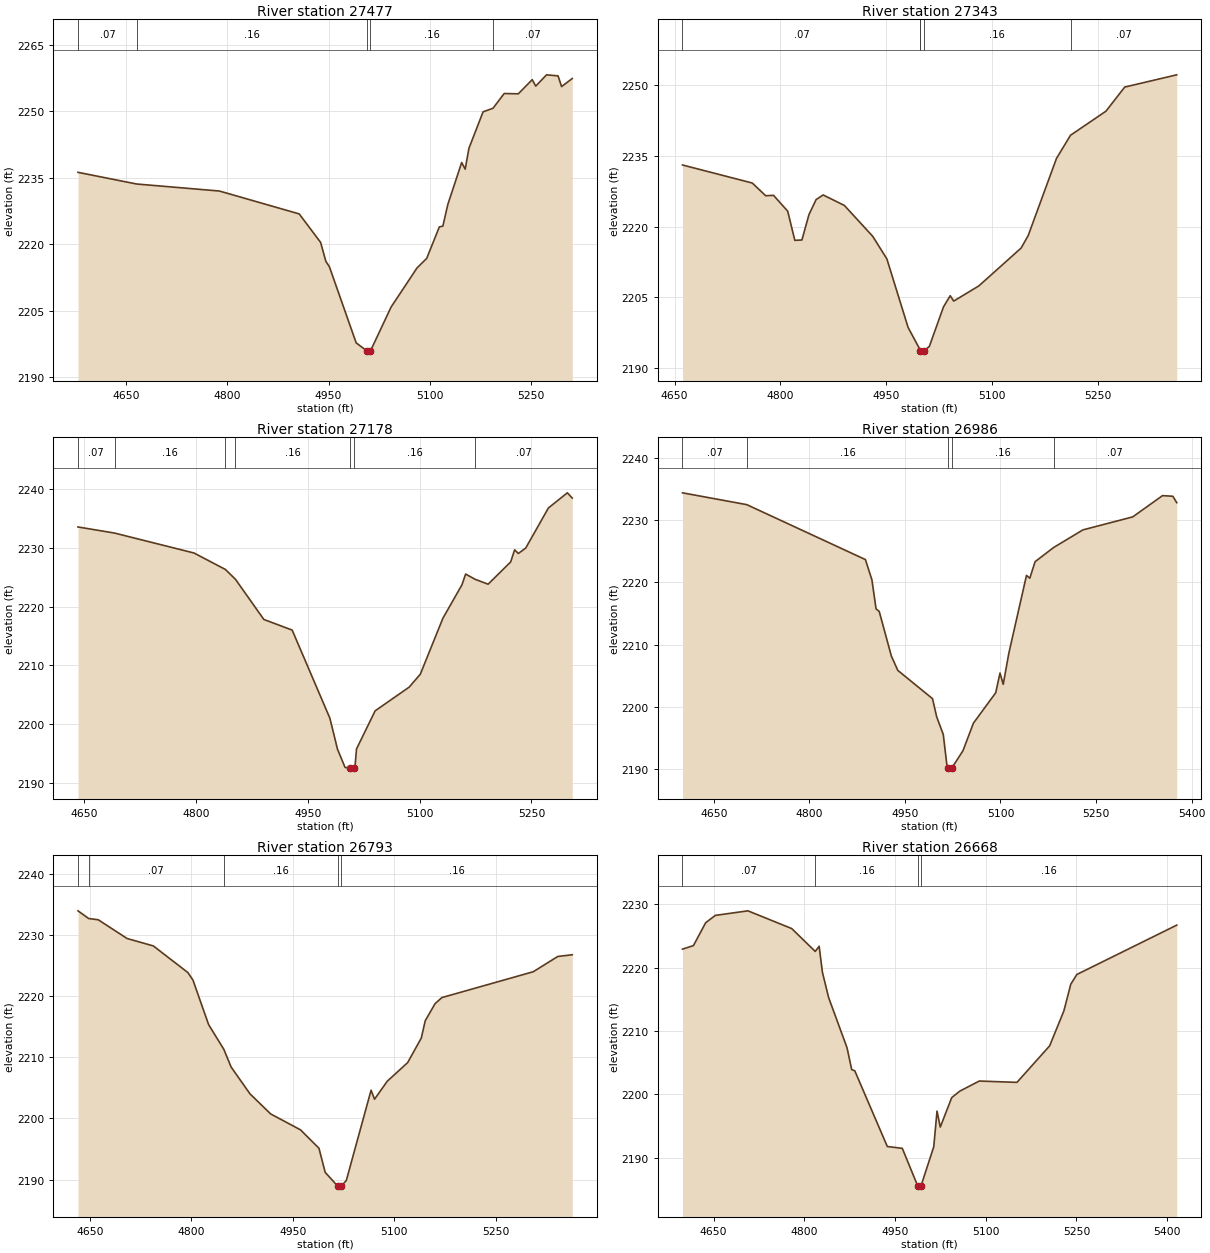
Type RM Length L Ch R = 1 ,27477   ,134,134,134
BEGIN DESCRIPTION:
712
END DESCRIPTION:
XS GIS Cut Line= 3
      1527612.53      6791828.75      1527747.08      6791427.27
      1527835.61      6791131.46
#Sta/Elev= 30
  4578.8 2236.24  4665.8  2233.6  4788.2 2232.02  4906.5 2226.85  4938.2 2220.42
    4946 2216.13  4951.2 2214.93  4990.9 2197.72  5006.9 2195.91  5007.3 2195.41
  5012.1 2195.91  5042.6 2205.81    5081 2214.64  5095.4 2216.81  5114.1 2223.91
  5119.3  2224.1  5126.7    2229  5147.2 2238.46  5152.4 2236.96    5158 2241.69
  5178.9  2249.9  5193.6 2250.71  5210.2 2254.04  5231.1 2253.97  5251.7 2257.17
  5256.9 2255.71  5272.9 2258.26    5290 2258.02  5295.2 2255.61    5311 2257.42
#Mann= 5 ,-1 , 0
  4578.8     .07       0  4665.8     .16       0  5006.9     .07       0
  5012.1     .16       0  5193.6     .07       0
Bank Sta=5006.9,5012.1
XS Rating Curve= 0 ,0
Exp/Cntr=0.3,0.1

Type RM Length L Ch R = 1 ,27343   ,165,165,165
BEGIN DESCRIPTION:
711
END DESCRIPTION:
XS GIS Cut Line= 3
      1527829.55      6791826.57      1527857.76      6791498.88
      1527872.95      6791127.79
#Sta/Elev= 30
  4661.2 2233.09  4760.1 2229.26  4779.1 2226.56  4790.2 2226.65  4810.3 2223.28
  4820.4 2217.09  4830.4 2217.17  4840.4 2222.55  4850.5 2225.74  4860.5 2226.73
  4890.6  2224.5  4930.8 2217.94  4950.8 2213.15  4980.9 2198.59    4998 2193.82
  4998.4 2193.65  4998.8 2193.15  5003.6 2193.65    5011 2194.58    5031 2202.96
  5040.5 2205.34  5045.5  2204.2  5081.1 2207.42  5141.1 2215.47  5151.1 2218.13
  5191.1 2234.48    5211  2239.4  5261.2 2244.51  5287.8 2249.63  5361.5 2252.23
#Mann= 5 ,-1 , 0
  4661.2     .07       0    4998     .16       0  4998.4     .07       0
  5003.6     .16       0    5211     .07       0
Bank Sta=4998.4,5003.6
XS Rating Curve= 0 ,0
Exp/Cntr=0.3,0.1

Type RM Length L Ch R = 1 ,27178   ,192,192,192
BEGIN DESCRIPTION:
710
END DESCRIPTION:
XS GIS Cut Line= 3
      1527951.07      6791891.69      1528009.67      6791524.92
       1528050.9      6791236.28
#Sta/Elev= 30
  4641.7 2233.55  4690.8 2232.51  4797.3 2229.12  4839.4 2226.32  4852.9 2224.65
    4891 2217.81    4929    2216  4979.6    2201  4989.8 2195.73  4999.9 2192.64
  5006.4  2192.5  5006.8    2192  5011.7  2192.5  5013.1  2192.5  5015.3 2195.77
  5040.3 2202.26    5086  2206.3  5100.9  2208.5  5131.2 2218.02  5156.7 2223.69
  5161.7 2225.54  5174.3 2224.65  5191.8 2223.81  5222.1  2227.6  5227.4 2229.66
  5232.4 2229.04  5242.3 2229.96  5272.7 2236.78  5298.1 2239.36  5304.7 2238.47
#Mann= 7 ,-1 , 0
  4641.7     .07       0  4690.8     .16       0  4839.4     .07       0
  4852.9     .16       0  5006.4     .07       0  5011.7     .16       0
  5174.3     .07       0
Bank Sta=5006.4,5011.7
XS Rating Curve= 0 ,0
Exp/Cntr=0.3,0.1

Type RM Length L Ch R = 1 ,26986   ,193,193,193
BEGIN DESCRIPTION:
709
END DESCRIPTION:
XS GIS Cut Line= 3
      1528116.01      6791980.61      1528185.45      6791594.37
      1528094.53      6791222.04
#Sta/Elev= 30
  4600.9 2234.41  4701.8 2232.51    4888 2223.68  4898.2 2220.42  4904.7 2215.76
  4909.7 2215.33  4928.7 2208.18  4938.8 2205.87  4993.3 2201.32  4999.9 2198.39
  5010.2 2195.56  5015.8 2190.72  5018.3 2190.17  5018.7 2189.67  5023.6 2190.17
  5041.1 2192.95  5057.5 2197.38  5092.5 2202.27  5099.2 2205.43  5104.3 2203.63
  5113.1 2208.63  5140.8 2221.13    5146 2220.68  5154.3 2223.34  5183.4 2225.62
  5229.3 2228.45  5307.5 2230.54  5354.3 2233.96  5370.5 2233.86  5376.6 2232.83
#Mann= 5 ,-1 , 0
  4600.9     .07       0  4701.8     .16       0  5018.3     .07       0
  5023.6     .16       0  5183.4     .07       0
Bank Sta=5018.3,5023.6
XS Rating Curve= 0 ,0
Exp/Cntr=0.3,0.1

Type RM Length L Ch R = 1 ,26793   ,125,125,125
BEGIN DESCRIPTION:
708
END DESCRIPTION:
XS GIS Cut Line= 3
      1528276.59       6791937.3      1528348.21      6791574.84
      1528302.64      6791216.79
#Sta/Elev= 30
  4632.5 2233.93  4648.3 2232.67  4662.4 2232.47    4705 2229.41  4743.9 2228.19
  4794.9 2223.84  4802.4 2222.61  4825.5 2215.34    4848  2211.3  4858.8  2208.4
  4886.6 2204.03  4917.2 2200.74  4961.3 2198.14  4988.6 2195.13  4997.8 2191.19
  5016.2 2188.95  5016.7 2188.45  5021.6 2188.95    5029 2189.86  5065.6 2204.61
  5070.7 2203.14  5089.5 2206.08  5119.7 2209.13  5139.9 2213.16  5145.6 2215.96
  5160.1 2218.75  5170.2 2219.75  5305.4 2223.98  5341.5 2226.47  5362.9 2226.75
#Mann= 5 ,-1 , 0
  4632.5     .16       0  4648.3     .07       0    4848     .16       0
  5016.2     .07       0  5021.6     .16       0
Bank Sta=5016.2,5021.6
XS Rating Curve= 0 ,0
Exp/Cntr=0.3,0.1

Type RM Length L Ch R = 1 ,26668   ,426,426,426
BEGIN DESCRIPTION:
707
END DESCRIPTION:
XS GIS Cut Line= 3
       1528400.3      6791995.82      1528469.74      6791607.39
       1528313.5      6791214.62
#Sta/Elev= 30
  4598.6 2222.92  4616.7 2223.48    4637  2227.1    4653 2228.25  4706.8 2228.97
  4779.2 2226.17  4818.1 2222.56  4824.6 2223.37    4830 2219.27  4840.2 2215.29
  4870.7 2207.35  4878.4  2203.9  4883.5 2203.71  4937.3 2191.75  4962.1 2191.46
  4987.6 2185.52  4988.1 2185.02    4993 2185.52  5014.1 2191.71  5019.5 2197.34
  5024.9 2194.82  5043.8 2199.47  5057.1 2200.49  5089.4 2202.09  5151.7 2201.88
  5205.7 2207.64  5229.3 2213.17  5240.7 2217.39  5250.8 2218.92  5415.9 2226.71
#Mann= 4 ,-1 , 0
  4598.6     .07       0  4818.1     .16       0  4987.6     .07       0
    4993     .16       0
Bank Sta=4987.6,4993
XS Rating Curve= 0 ,0
Exp/Cntr=0.3,0.1

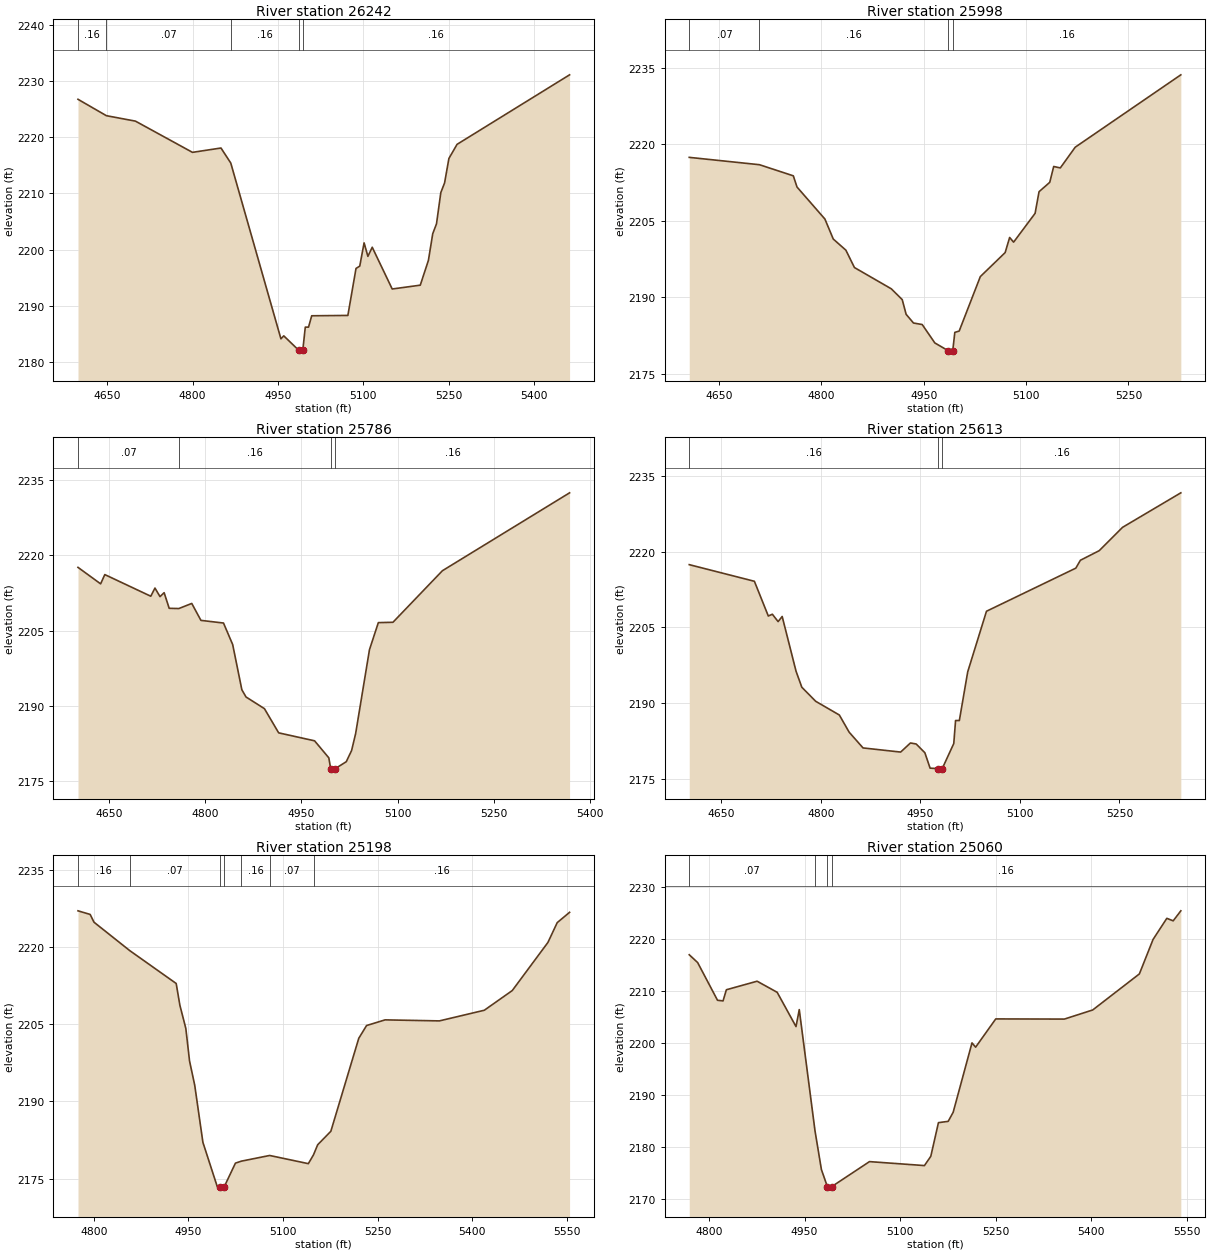
Type RM Length L Ch R = 1 ,26242   ,244,244,244
BEGIN DESCRIPTION:
706
END DESCRIPTION:
XS GIS Cut Line= 3
      1529055.72      6791464.16       1528654.2      6791440.29
      1528306.99      6791136.48
#Sta/Elev= 30
  4598.7 2226.72  4648.5 2223.81  4699.6 2222.84  4799.8 2217.29  4849.9 2218.06
  4867.1 2215.39  4955.2 2184.14  4960.2 2184.67  4986.6  2182.1  4987.1  2181.6
  4993.6  2182.1    4998 2186.22  5003.7 2186.22  5009.3 2188.24  5072.8  2188.3
  5087.1 2196.65  5093.7 2197.07  5101.3  2201.2    5108  2198.8  5115.6 2200.42
  5150.7    2193    5200 2193.68  5214.3 2198.09  5221.9 2202.83  5228.5 2204.58
  5236.1 2210.14  5242.7 2211.86  5250.3  2216.2  5264.6 2218.71  5462.3 2231.07
#Mann= 5 ,-1 , 0
  4598.7     .16       0  4648.5     .07       0  4867.1     .16       0
  4986.6     .07       0  4993.6     .16       0
Bank Sta=4986.6,4993.6
XS Rating Curve= 0 ,0
Exp/Cntr=0.3,0.1

Type RM Length L Ch R = 1 ,25998   ,212,212,212
BEGIN DESCRIPTION:
705
END DESCRIPTION:
XS GIS Cut Line= 3
      1528968.86      6791362.16      1528606.46      6791212.42
      1528322.15      6791047.49
#Sta/Elev= 30
  4606.1 2217.46    4709 2216.02  4758.7 2213.84  4764.1 2211.64    4805 2205.36
  4817.3 2201.43  4835.8 2199.24  4848.3 2195.84  4902.4 2191.66  4918.4 2189.54
  4924.1 2186.66  4934.9 2184.95  4947.7 2184.65  4966.2 2181.04  4985.5 2179.54
    4986 2179.04  4992.5 2179.54  4995.5 2183.11  5001.9 2183.37  5032.9 2194.06
  5069.3 2198.77  5075.9 2201.74  5081.7 2200.82  5113.2 2206.47    5119 2210.72
  5134.7 2212.56  5140.5 2215.67  5150.2 2215.39    5172 2219.45  5326.9 2233.66
#Mann= 4 ,-1 , 0
  4606.1     .07       0    4709     .16       0  4985.5     .07       0
  4992.5     .16       0
Bank Sta=4985.5,4992.5
XS Rating Curve= 0 ,0
Exp/Cntr=0.3,0.1

Type RM Length L Ch R = 1 ,25786   ,173,173,173
BEGIN DESCRIPTION:
704
END DESCRIPTION:
XS GIS Cut Line= 3
      1528992.73      6791359.98      1528736.67      6791049.66
      1528517.47      6790758.85
#Sta/Elev= 30
  4601.7 2217.61    4637 2214.32  4643.5 2216.17  4715.2 2211.85  4721.7 2213.48
  4729.6 2211.77    4736 2212.56  4743.9 2209.44  4758.9 2209.39  4779.1 2210.41
  4793.4 2207.03  4828.6  2206.5  4842.9  2202.2  4857.2 2193.18  4863.7 2191.74
  4892.4 2189.41  4914.6 2184.58  4970.6 2182.99  4992.8 2179.59  4995.7 2177.44
  4996.2 2176.94  5002.8 2177.44    5020 2178.82  5028.3 2181.05  5034.6 2184.42
  5056.2 2201.19    5070 2206.58  5092.8 2206.65  5169.9 2216.94  5368.2 2232.49
#Mann= 4 ,-1 , 0
  4601.7     .07       0  4758.9     .16       0  4995.7     .07       0
  5002.8     .16       0
Bank Sta=4995.7,5002.8
XS Rating Curve= 0 ,0
Exp/Cntr=0.3,0.1

Type RM Length L Ch R = 1 ,25613   ,415,415,415
BEGIN DESCRIPTION:
703
END DESCRIPTION:
XS GIS Cut Line= 3
      1529059.99      6791238.44      1528827.81       6790908.6
      1528595.59      6790663.36
#Sta/Elev= 30
  4601.5 2217.43  4699.7 2214.14  4720.7 2207.27  4726.8 2207.62  4735.5 2206.16
  4741.6 2207.18  4762.5 2196.35  4771.2 2193.18  4792.1  2190.4  4827.8 2187.68
  4842.6 2184.28  4863.5 2181.17  4920.2 2180.35    4935 2182.15  4943.6 2181.95
  4956.7 2180.22  4964.6 2177.17  4975.8 2177.08  4976.3 2176.58  4982.9 2177.08
  5000.3 2182.04    5003 2186.59  5008.7 2186.59  5021.3 2196.22  5049.6 2208.21
  5184.3 2216.74  5191.2  2218.3  5219.5 2220.19  5254.7 2224.81  5342.6 2231.64
#Mann= 3 ,-1 , 0
  4601.5     .16       0  4975.8     .07       0  4982.9     .16       0
Bank Sta=4975.8,4982.9
XS Rating Curve= 0 ,0
Exp/Cntr=0.3,0.1

Type RM Length L Ch R = 1 ,25198   ,138,138,138
BEGIN DESCRIPTION:
702
END DESCRIPTION:
XS GIS Cut Line= 3
      1529263.78      6791144.26       1529081.5      6790857.82
      1528722.37      6790602.79
#Sta/Elev= 30
  4774.7 2227.02    4794 2226.32  4800.1 2224.81  4856.7  2219.3  4930.5  2212.9
  4936.4 2208.65  4945.8 2204.17  4951.7 2197.84  4959.9 2193.14  4972.9 2182.03
  4995.5 2173.49  4999.8 2173.44  5000.3 2172.94  5006.9 2173.44  5024.5 2177.99
  5034.1 2178.38  5078.8 2179.48  5140.2 2177.89  5148.4 2179.61    5155 2181.56
  5175.9 2184.18  5220.2 2202.25  5232.6 2204.73    5262 2205.83  5348.1 2205.63
  5419.4  2207.7  5463.7 2211.52  5520.3 2220.87  5535.1 2224.73  5554.7 2226.73
#Mann= 7 ,-1 , 0
  4774.7     .16       0  4856.7     .07       0  4999.8     .07       0
  5006.9     .07       0  5034.1     .16       0  5078.8     .07       0
  5148.4     .16       0
Bank Sta=4999.8,5006.9
XS Rating Curve= 0 ,0
Exp/Cntr=0.3,0.1

Type RM Length L Ch R = 1 ,25060   ,250,250,250
BEGIN DESCRIPTION:
701
END DESCRIPTION:
XS GIS Cut Line= 3
      1529427.88      6790917.73      1529196.08      6790855.22
      1528735.12      6790589.58
#Sta/Elev= 30
  4768.9 2216.97  4782.1 2215.47  4813.3 2208.23    4822 2208.11  4827.2 2210.25
  4875.5 2211.89    4907 2209.76  4936.6 2203.18  4941.7 2206.44  4966.5  2183.1
  4976.5 2175.73  4985.8 2172.48  4986.3 2171.98  4992.9 2172.48    5052 2177.26
  5138.3  2176.5  5148.3 2178.28  5160.3 2184.74  5175.6 2184.99  5183.4 2186.72
    5213 2200.05  5218.7 2199.23  5250.3 2204.65  5358.1 2204.62  5402.6 2206.37
  5475.9 2213.29  5497.4 2219.91    5519 2223.96    5529 2223.48    5541  2225.4
#Mann= 4 ,-1 , 0
  4768.9     .07       0  4966.5     .16       0  4985.8     .07       0
  4992.9     .16       0
Bank Sta=4985.8,4992.9
XS Rating Curve= 0 ,0
Exp/Cntr=0.3,0.1

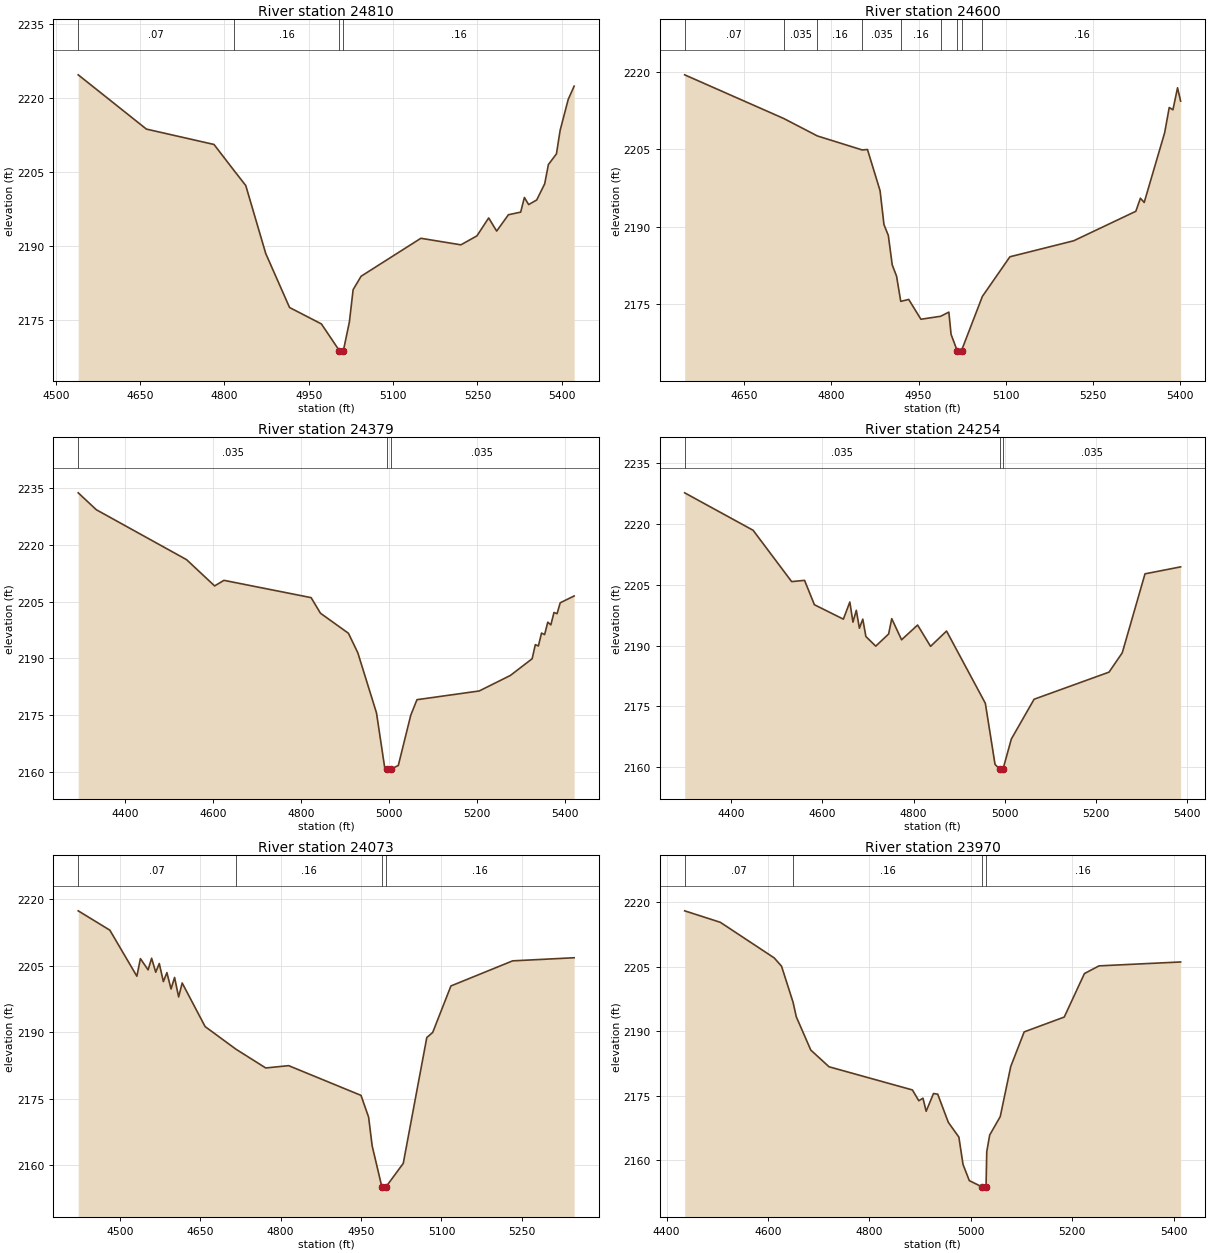
Type RM Length L Ch R = 1 ,24810   ,210,210,210
BEGIN DESCRIPTION:
700
END DESCRIPTION:
XS GIS Cut Line= 3
      1529495.56      6790948.97      1529164.83      6790623.45
      1528889.43      6790309.07
#Sta/Elev= 30
    4540 2224.71  4661.3 2213.69  4781.5 2210.57    4817  2205.3    4838 2202.23
  4873.5 2188.43  4915.9 2177.46  4972.5 2174.13  5004.5  2168.7    5005  2168.2
  5011.6  2168.7  5022.3 2174.55  5028.9 2181.08  5043.1 2183.81  5149.4 2191.52
  5220.6 2190.19  5249.1 2192.01    5270 2195.65  5284.2 2192.98  5305.1  2196.3
  5326.9 2196.83  5333.5 2199.81  5341.1 2198.36  5355.4  2199.3  5369.6 2202.58
  5376.2 2206.49  5390.5 2208.66  5397.1 2213.45  5411.4  2219.7    5422 2222.41
#Mann= 4 ,-1 , 0
    4540     .07       0    4817     .16       0  5004.5     .07       0
  5011.6     .16       0
Bank Sta=5004.5,5011.6
XS Rating Curve= 0 ,0
Exp/Cntr=0.3,0.1

Type RM Length L Ch R = 1 ,24600   ,221,221,221
BEGIN DESCRIPTION:
699
END DESCRIPTION:
XS GIS Cut Line= 4
      1529558.05      6790779.68      1529255.98      6790443.76
      1529063.22      6790424.77      1528901.89      6790292.93
#Sta/Elev= 30
  4547.3 2219.44  4717.9 2210.98  4775.8  2207.6    4853 2204.89    4862 2204.98
  4883.7 2196.99  4890.4 2190.43  4897.9 2188.33  4904.6 2182.64  4912.1 2180.43
  4919.3 2175.56    4933 2175.94    4954  2172.1    4988 2172.68  5002.1 2173.48
  5005.9 2169.19  5016.4 2166.04  5016.9 2165.54  5023.9 2166.04  5059.8 2176.52
  5107.2  2184.2    5217  2187.3    5324 2193.01  5331.9 2195.54  5338.4 2194.72
  5373.6 2208.22  5381.5 2213.11  5387.9 2212.67  5395.8 2216.93  5401.1 2214.36
#Mann= 9 ,-1 , 0
  4547.3     .07       0  4717.9    .035       0  4775.8     .16       0
    4853    .035       0  4919.3     .16       0    4988    .035       0
  5016.4    .035       0  5023.9    .035       0  5059.8     .16       0
Bank Sta=5016.4,5023.9
XS Rating Curve= 0 ,0
Exp/Cntr=0.3,0.1

Type RM Length L Ch R = 1 ,24379   ,125,125,125
BEGIN DESCRIPTION:
697
END DESCRIPTION:
XS GIS Cut Line= 3
      1529870.11        6790771.      1529379.68      6790276.23
      1529080.17      6789968.04
#Sta/Elev= 30
  4293.5  2233.8  4334.6 2229.33  4539.6 2216.12  4603.3 2209.17  4624.5 2210.65
  4822.5 2206.07  4843.7 2201.95  4907.3 2196.64  4928.6 2191.47    4971 2175.56
  4989.9 2160.88  4995.5 2160.67    4996 2160.17  5003.1 2160.67  5020.5 2161.66
  5048.8 2174.96  5062.9 2179.07  5204.4 2181.38  5275.1 2185.49  5324.5  2189.9
  5331.7 2193.63  5338.7 2193.28  5345.8  2196.7  5352.8 2196.29    5360 2199.58
    5367 2198.86  5374.1 2202.14  5381.1 2201.83  5388.3 2204.71  5419.9 2206.51
#Mann= 3 ,-1 , 0
  4293.5    .035       0  4995.5    .035       0  5003.1    .035       0
Bank Sta=4995.5,5003.1
XS Rating Curve= 0 ,0
Exp/Cntr=0.3,0.1

Type RM Length L Ch R = 1 ,24254   ,181,181,181
BEGIN DESCRIPTION:
698
END DESCRIPTION:
XS GIS Cut Line= 3
      1529904.86      6790679.88      1529431.76      6790163.38
      1529123.59        6789929.
#Sta/Elev= 30
    4298 2227.75  4448.1  2218.5  4532.6 2205.82  4560.9 2206.13  4582.5 2200.11
    4646 2196.55  4660.2 2200.78    4667 2195.82  4674.4 2198.73  4681.2 2194.31
  4688.6 2196.56  4695.4 2192.26    4717 2189.88  4745.3 2192.89  4752.1 2196.67
  4773.7 2191.45  4808.8 2195.09  4837.2 2189.83  4872.3 2193.61  4957.4 2175.76
  4978.6 2160.69  4988.5 2159.51    4989 2159.01  4996.1 2159.51  5014.4 2166.95
  5064.3 2176.77  5228.6 2183.46  5257.6 2188.23  5307.5 2207.74  5385.6 2209.46
#Mann= 3 ,-1 , 0
    4298    .035       0  4988.5    .035       0  4996.1    .035       0
Bank Sta=4988.5,4996.1
XS Rating Curve= 0 ,0
Exp/Cntr=0.3,0.1

Type RM Length L Ch R = 1 ,24073   ,103,103,103
BEGIN DESCRIPTION:
696
END DESCRIPTION:
XS GIS Cut Line= 3
      1529935.24      6790471.54      1529548.95      6790024.49
      1529245.12       6789885.6
#Sta/Elev= 30
  4422.6 2217.34  4481.6 2212.98    4532  2202.6  4538.6 2206.56  4552.9 2204.03
  4559.5 2206.65  4567.2  2203.5  4573.8 2205.46  4581.4 2201.39    4588 2203.41
  4595.7 2199.72  4602.3 2202.32  4609.9 2197.92  4616.5 2201.07  4659.3 2191.24
  4716.7 2186.15  4772.3 2181.91  4815.1 2182.43    4950 2175.73  4964.2 2170.81
  4970.8 2164.35  4988.9 2155.09  4989.4 2154.59  4996.5 2155.09  5028.8  2160.4
  5072.7 2188.77  5083.7 2189.92  5117.7  2200.4  5232.8 2206.06  5347.5 2206.76
#Mann= 4 ,-1 , 0
  4422.6     .07       0  4716.7     .16       0  4988.9     .07       0
  4996.5     .16       0
Bank Sta=4988.9,4996.5
XS Rating Curve= 0 ,0
Exp/Cntr=0.3,0.1

Type RM Length L Ch R = 1 ,23970   ,176,176,176
BEGIN DESCRIPTION:
695
END DESCRIPTION:
XS GIS Cut Line= 3
      1529974.32      6790406.47      1529640.09      6789963.73
      1529232.14      6789850.89
#Sta/Elev= 30
  4435.7 2218.05    4506 2215.38  4612.2  2207.1  4626.7 2205.17  4649.5 2196.75
  4655.8  2193.4  4684.4 2185.65  4720.4 2181.76  4884.8 2176.37  4897.4 2173.86
  4905.6 2174.45  4911.9 2171.41  4926.4 2175.54  4934.7 2175.39  4955.6 2168.84
  4976.4  2165.4  4984.6 2159.04    4997 2155.27  5022.4 2153.79  5022.9 2153.29
    5030 2153.79  5031.4 2162.01  5037.2 2165.88    5058 2170.17  5078.7 2181.82
  5105.2 2189.88  5184.2 2193.33    5224 2203.45  5252.8 2205.24  5413.7 2206.15
#Mann= 4 ,-1 , 0
  4435.7     .07       0  4649.5     .16       0  5022.4     .07       0
    5030     .16       0
Bank Sta=5022.4,5030
XS Rating Curve= 0 ,0
Exp/Cntr=0.3,0.1

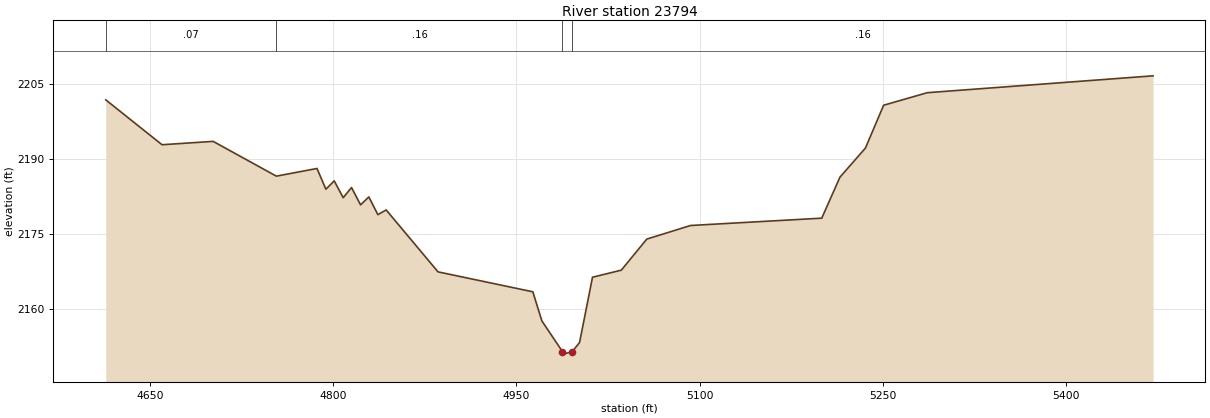
Type RM Length L Ch R = 1 ,23794   ,195,195,195
BEGIN DESCRIPTION:
694
END DESCRIPTION:
XS GIS Cut Line= 3
      1530039.43       6790098.3      1529757.28      6789837.86
      1529366.68      6789568.77
#Sta/Elev= 30
  4613.4 2201.75  4659.5 2192.81  4701.4 2193.48  4753.2 2186.55  4786.5 2188.08
  4793.8 2183.95  4800.6 2185.61    4808 2182.26  4814.8 2184.29  4822.2 2180.83
    4829 2182.41  4836.4 2178.88  4843.2 2179.82  4885.7 2167.48  4963.4 2163.51
  4970.8 2157.71  4987.7 2151.59  4988.2 2151.09  4995.7 2151.59  5001.7 2153.41
  5012.3 2166.41  5035.9 2167.82  5056.8 2174.01  5092.7 2176.72  5200.2 2178.18
  5215.1 2186.35    5236 2192.15  5250.9 2200.68  5286.7 2203.18  5471.7 2206.54
#Mann= 4 ,-1 , 0
  4613.4     .07       0  4753.2     .16       0  4987.7     .07       0
  4995.7     .16       0
Bank Sta=4987.7,4995.7
XS Rating Curve= 0 ,0
Exp/Cntr=0.3,0.1