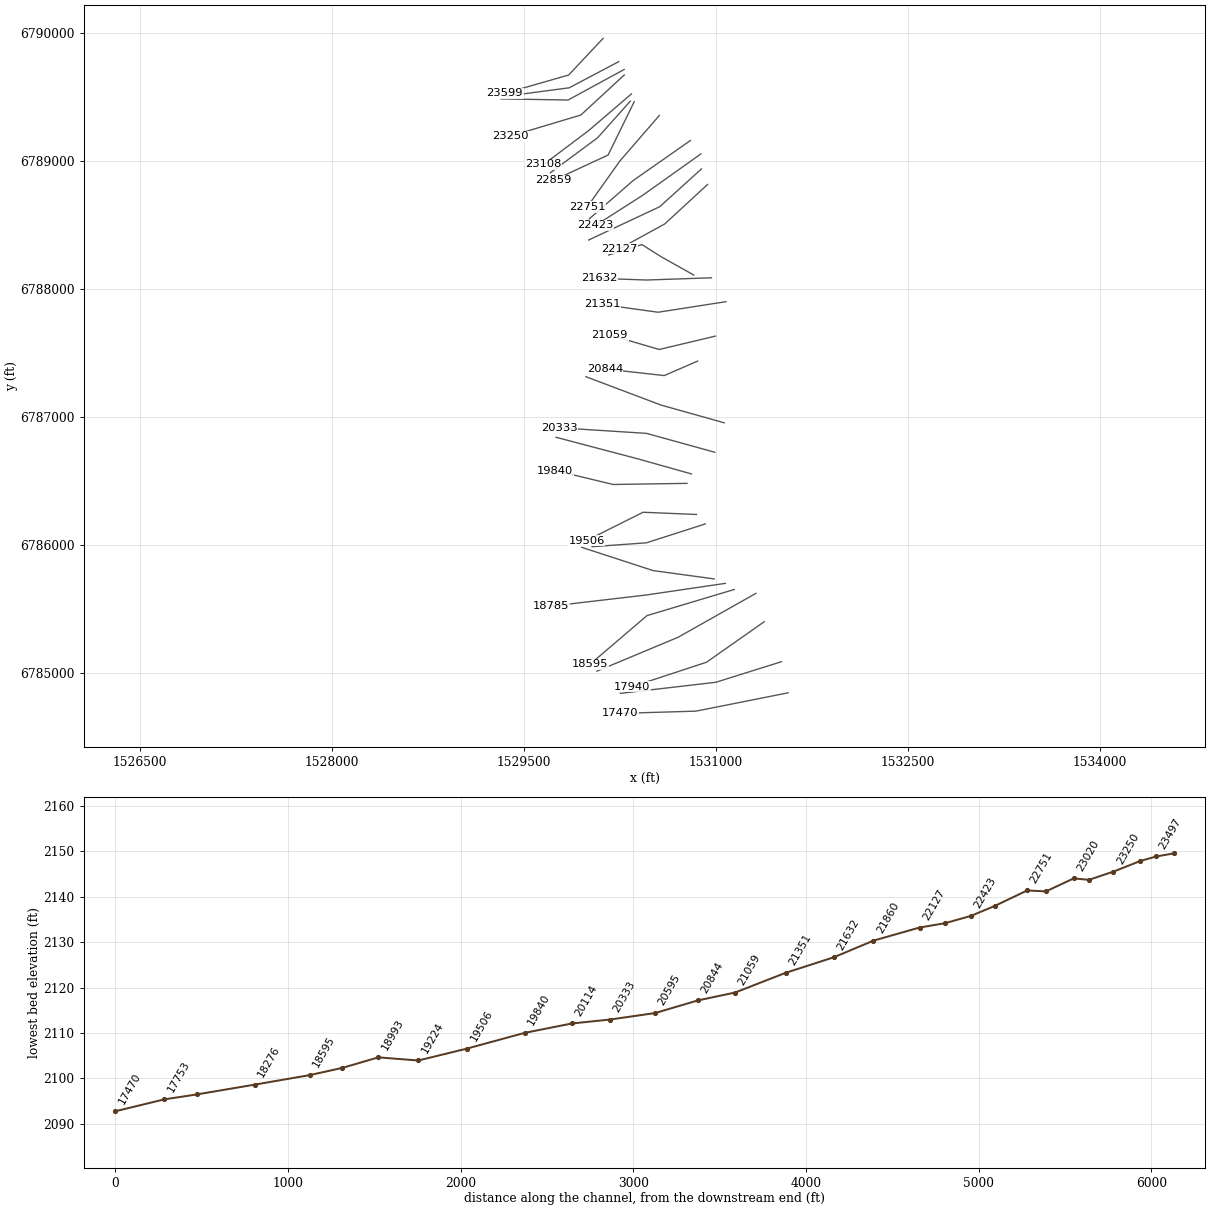
HEC-RAS study Elm 85.prj: Elm 85 Base Level Engineering

--- Elm 85.g01 (geometry) --- (continued)

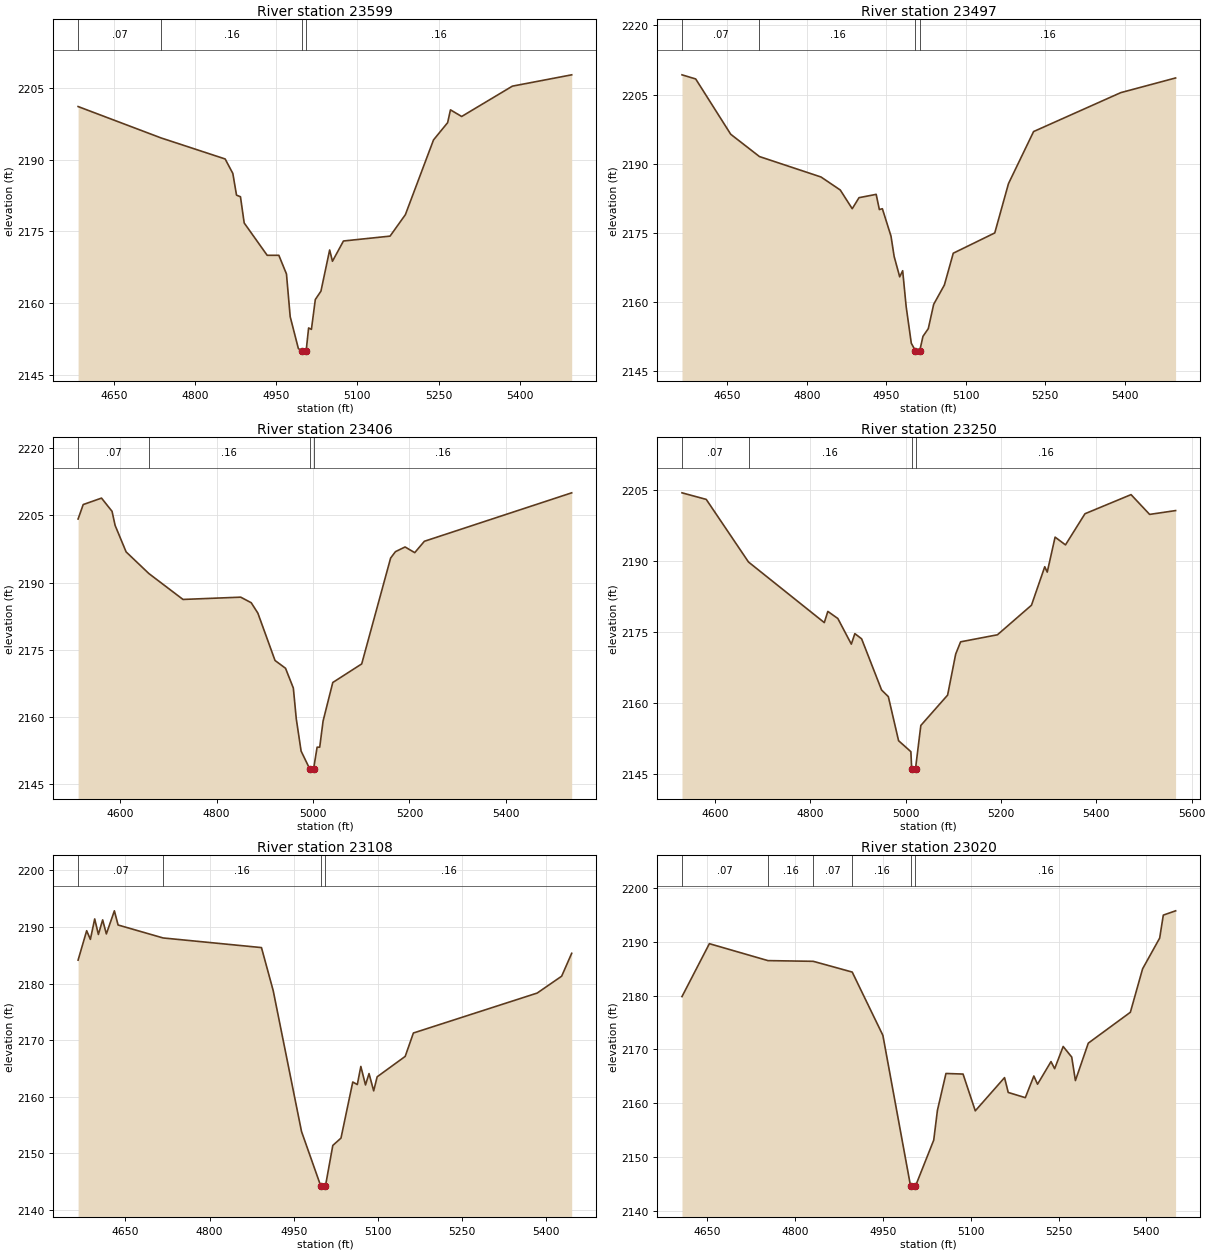
Type RM Length L Ch R = 1 ,23599   ,102,102,102
BEGIN DESCRIPTION:
692
END DESCRIPTION:
XS GIS Cut Line= 3
      1530117.56      6789959.42      1529848.43      6789672.93
      1529349.63       6789529.8
#Sta/Elev= 30
  4584.1 2201.13  4737.2 2194.57  4855.8 2190.16    4870 2187.13  4876.8 2182.59
  4884.1 2182.25    4891 2176.76  4933.5 2169.99    4955    2170  4969.1 2166.09
    4976 2157.14  4991.1 2150.47  4997.5 2150.02    4998 2149.52  5005.5 2150.02
    5010 2154.79  5015.2 2154.49  5022.4 2160.74  5032.8 2162.49  5048.9 2171.11
  5054.1 2168.75  5074.4 2172.99  5160.5 2174.01  5188.8  2178.5  5240.8 2194.15
  5266.9 2197.76  5272.1 2200.44  5292.8 2199.05  5386.5  2205.4  5496.1 2207.77
#Mann= 4 ,-1 , 0
  4584.1     .07       0  4737.2     .16       0  4997.5     .07       0
  5005.5     .16       0
Bank Sta=4997.5,5005.5
XS Rating Curve= 0 ,0
Exp/Cntr=0.3,0.1

Type RM Length L Ch R = 1 ,23497   ,91,91,91
BEGIN DESCRIPTION:
693
END DESCRIPTION:
XS GIS Cut Line= 3
      1530239.09      6789777.12      1529852.77       6789573.1
      1529362.36        6789508.
#Sta/Elev= 30
  4564.6 2209.28  4590.5 2208.38  4656.6 2196.37  4710.8 2191.53    4827 2187.09
  4863.3 2184.27  4885.9  2180.2  4898.7  2182.6  4931.1 2183.32  4937.1 2180.02
  4942.8  2180.2  4959.1 2174.24    4965 2169.84  4975.5 2165.41  4981.1 2166.74
  4987.7 2158.93  4997.4 2150.98  5005.3 2149.34  5005.8 2148.84  5013.3 2149.34
  5019.4 2152.48  5029.5 2154.17  5039.6 2159.43  5059.8 2163.63  5076.6 2170.54
  5154.9 2174.94  5180.8 2185.65  5228.2 2196.96  5392.7 2205.41  5496.2  2208.6
#Mann= 4 ,-1 , 0
  4564.6     .07       0  4710.8     .16       0  5005.3     .07       0
  5013.3     .16       0
Bank Sta=5005.3,5013.3
XS Rating Curve= 0 ,0
Exp/Cntr=0.3,0.1

Type RM Length L Ch R = 1 ,23406   ,156,156,156
BEGIN DESCRIPTION:
691
END DESCRIPTION:
XS GIS Cut Line= 3
      1530282.46      6789716.34      1529844.09      6789477.62
      1529319.42      6789486.29
#Sta/Elev= 30
  4512.8  2204.2  4523.4 2207.43  4561.4 2208.87  4583.2 2205.92  4589.6 2202.77
  4612.4 2196.85  4659.5 2192.02  4730.4 2186.22  4850.1 2186.73  4871.9 2185.49
  4885.7 2183.17  4921.3 2172.58  4943.1 2170.84  4959.3 2166.41  4965.4 2159.53
  4975.4 2152.33  4993.3 2148.35  4993.8 2147.85  5001.3 2148.35  5008.6  2153.2
    5014  2153.2    5021 2159.05  5041.1 2167.66  5101.1 2171.81  5161.1 2195.47
  5171.1  2196.9  5191.1 2197.95  5211.1 2196.68  5231.1 2199.22  5536.7 2210.05
#Mann= 4 ,-1 , 0
  4512.8     .07       0  4659.5     .16       0  4993.3     .07       0
  5001.3     .16       0
Bank Sta=4993.3,5001.3
XS Rating Curve= 0 ,0
Exp/Cntr=0.3,0.1

Type RM Length L Ch R = 1 ,23250   ,142,142,142
BEGIN DESCRIPTION:
690
END DESCRIPTION:
XS GIS Cut Line= 3
      1530282.42       6789672.9      1529943.91      6789360.43
      1529392.74      6789195.51
#Sta/Elev= 30
  4530.3 2204.44  4581.2 2203.05  4669.9 2189.79    4829 2176.96  4836.4 2179.33
  4857.4 2177.83  4885.7  2172.4  4893.1 2174.62  4907.3 2173.53  4949.2 2162.69
  4963.4 2161.28  4984.9 2151.95  5010.7 2149.63  5012.4 2146.01  5012.9 2145.51
  5020.4 2146.01  5031.6 2155.18  5087.8 2161.61  5104.7 2170.28  5115.1 2172.89
  5192.4 2174.38  5263.8 2180.64  5291.7 2188.79  5296.9 2187.65  5313.4 2195.06
  5335.2 2193.42  5376.1 2200.01  5472.8 2204.06  5511.8 2199.87  5566.3 2200.68
#Mann= 4 ,-1 , 0
  4530.3     .07       0  4669.9     .16       0  5012.4     .07       0
  5020.4     .16       0
Bank Sta=5012.4,5020.4
XS Rating Curve= 0 ,0
Exp/Cntr=0.3,0.1

Type RM Length L Ch R = 1 ,23108   ,88,88,88
BEGIN DESCRIPTION:
688
END DESCRIPTION:
XS GIS Cut Line= 3
      1530338.85      6789525.34      1530004.68       6789238.9
      1529653.15      6788974.17
#Sta/Elev= 30
  4565.5 2184.13  4580.8 2189.32  4587.4 2187.79  4595.1  2191.4  4601.7 2188.66
  4609.3 2191.23  4615.9 2188.75  4630.2 2192.83  4636.8 2190.33  4717.1 2188.04
  4892.5 2186.34  4913.4 2178.75  4963.9 2153.88  4998.4  2144.2  4998.9  2143.7
  5006.5  2144.2  5019.7 2151.41  5034.3 2152.71  5055.3 2162.61  5063.4 2162.16
  5069.7 2165.36    5078 2162.09  5084.3  2164.1  5092.6 2161.05  5098.8 2163.53
  5148.8 2167.13  5163.4 2171.26  5384.1 2178.31  5427.8 2181.29  5445.7 2185.33
#Mann= 4 ,-1 , 0
  4565.5     .07       0  4717.1     .16       0  4998.4     .07       0
  5006.5     .16       0
Bank Sta=4998.4,5006.5
XS Rating Curve= 0 ,0
Exp/Cntr=0.3,0.1

Type RM Length L Ch R = 1 ,23020   ,161,161,161
BEGIN DESCRIPTION:
689
END DESCRIPTION:
XS GIS Cut Line= 3
      1530330.21      6789468.94      1530074.12      6789182.48
      1529705.16      6788909.01
#Sta/Elev= 30
  4606.5 2179.83  4653.3 2189.67  4753.4 2186.52  4830.8 2186.39  4897.4 2184.39
  4949.8 2172.62  4997.2 2144.52  4997.7 2144.02  5005.3 2144.52  5036.7 2153.14
    5043 2158.67  5057.6 2165.53  5086.8 2165.42  5107.7 2158.58  5157.7 2164.76
    5164    2162  5193.2 2161.03  5207.8 2165.06  5214.1 2163.53  5237.1 2167.74
  5243.3 2166.42  5257.9 2170.55  5272.5 2168.58  5278.8 2164.21  5300.8 2171.17
  5372.7 2176.91  5393.6 2184.99  5422.8 2190.71    5429 2194.98    5450 2195.78
#Mann= 6 ,-1 , 0
  4606.5     .07       0  4753.4     .16       0  4830.8     .07       0
  4897.4     .16       0  4997.2     .07       0  5005.3     .16       0
Bank Sta=4997.2,5005.3
XS Rating Curve= 0 ,0
Exp/Cntr=0.3,0.1

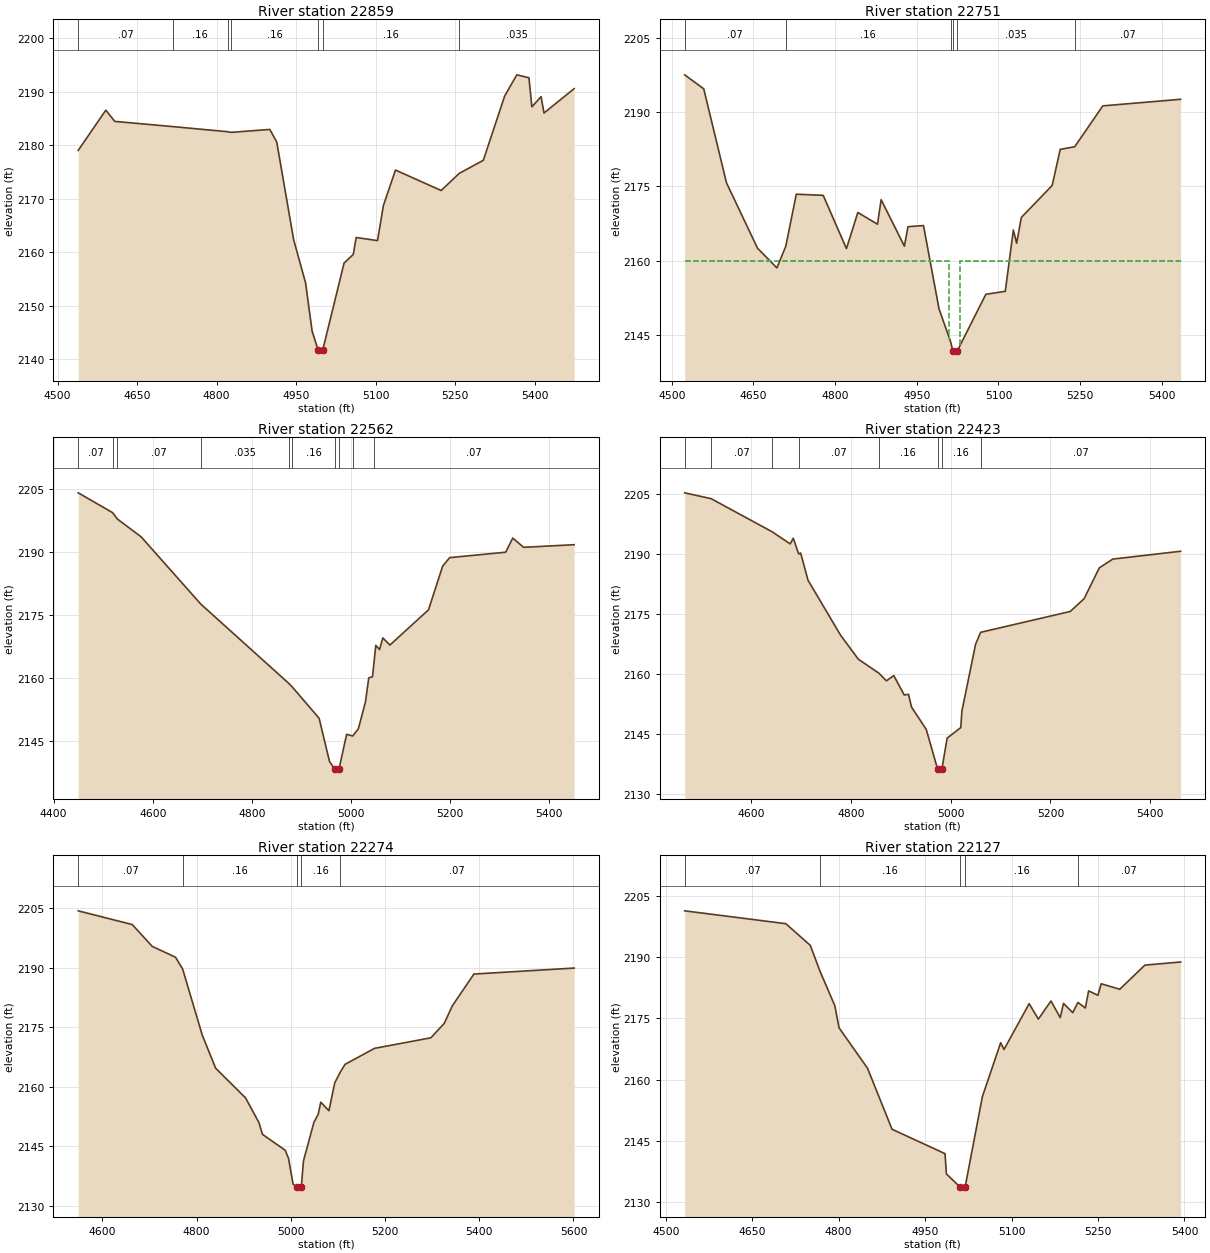
Type RM Length L Ch R = 1 ,22859   ,108,108,108
BEGIN DESCRIPTION:
686
END DESCRIPTION:
XS GIS Cut Line= 3
      1530360.56      6789464.56      1530156.59      6789047.93
      1529728.43      6788848.99
#Sta/Elev= 30
  4538.8 2179.02  4590.9 2186.54  4607.8 2184.44    4717 2183.47    4821 2182.51
  4827.6 2182.39  4900.4 2182.94  4913.5 2180.59  4945.4 2162.34  4967.9 2154.28
  4980.3 2145.23  4991.9 2141.65  4992.4 2141.15  5000.1 2141.65  5040.6 2157.98
  5057.9 2159.59  5063.5 2162.75  5103.7 2162.17  5114.8 2168.73  5137.6 2175.35
  5223.7 2171.53    5258 2174.73  5303.4 2177.18  5343.7 2189.19  5366.6 2193.14
  5389.5 2192.59    5395 2187.16  5412.4 2189.06  5417.9 2186.01  5474.8 2190.56
#Mann= 7 ,-1 , 0
  4538.8     .07       0    4717     .16       0    4821     .07       0
  4827.6     .16       0  4991.9     .07       0  5000.1     .16       0
    5258    .035       0
Bank Sta=4991.9,5000.1
XS Rating Curve= 0 ,0
Exp/Cntr=0.3,0.1

Type RM Length L Ch R = 1 ,22751   ,189,189,189
BEGIN DESCRIPTION:
687
END DESCRIPTION:
XS GIS Cut Line= 3
      1530555.87      6789356.06      1530247.73      6789000.18
      1529992.77      6788641.51
#Sta/Elev= 30
  4523.7 2197.48  4558.7 2194.66  4600.5  2175.7  4657.5 2162.52  4693.1 2158.55
  4709.4 2162.93  4728.7 2173.41  4778.1 2173.18  4820.8 2162.44  4841.7 2169.73
  4877.8 2167.36  4884.5  2172.3  4927.2 2162.94  4933.8 2166.86  4962.3 2167.09
  4990.8  2150.3  5012.3 2143.59    5016 2141.87  5016.5 2141.37  5024.6 2141.87
  5076.8 2153.23  5112.5 2153.83  5127.3 2166.19  5133.4 2163.53    5142 2168.73
  5198.6 2175.17  5213.4 2182.45    5240 2182.98  5291.6 2191.22  5434.5 2192.55
#Mann= 6 ,-1 , 0
  4523.7     .07       0  4709.4     .16       0  5012.3    .035       0
    5016     .07       0  5024.6    .035       0    5240     .07       0
#XS Ineff= 2 , 0
       0    5010    2160    5030       0    2160
Permanent Ineff=
       F       F
Bank Sta=5016,5024.6
XS Rating Curve= 0 ,0
Exp/Cntr=0.3,0.1

Type RM Length L Ch R = 1 ,22562   ,139,139,139
BEGIN DESCRIPTION:
684
END DESCRIPTION:
XS GIS Cut Line= 3
      1530798.97      6789160.79       1530351.9      6788848.27
      1530009.49      6788549.21
#Sta/Elev= 30
  4449.8 2204.03    4519 2199.33    4529 2197.79  4576.7 2193.58  4696.9 2177.62
  4874.8 2158.74  4881.9 2157.87  4935.6 2150.49  4956.6 2140.21  4967.1 2138.44
  4967.6 2137.94  4975.7 2138.44  4991.1 2146.69  5003.3 2146.28  5014.8 2148.01
    5029 2154.36  5035.7 2160.08  5043.3 2160.36  5047.1 2164.65  5049.9 2167.81
  5057.5 2166.81  5064.1 2169.58  5078.4 2167.88  5156.2 2176.25  5184.7 2186.61
  5198.9 2188.64  5311.9 2189.93  5326.1 2193.29    5348 2191.09  5449.9 2191.71
#Mann= 10 ,-1 , 0
  4449.8     .07       0    4519    .035       0    4529     .07       0
  4696.9    .035       0  4874.8     .07       0  4881.9     .16       0
  4967.1     .07       0  4975.7     .16       0  5003.3    .035       0
  5047.1     .07       0
Bank Sta=4967.1,4975.7
XS Rating Curve= 0 ,0
Exp/Cntr=0.3,0.1

Type RM Length L Ch R = 1 ,22423   ,149,149,149
BEGIN DESCRIPTION:
685
END DESCRIPTION:
XS GIS Cut Line= 3
      1530881.39      6789056.59      1530430.02      6788735.43
      1530058.39      6788497.76
#Sta/Elev= 30
  4466.2 2205.22  4519.3 2203.76  4641.5 2195.51    4678 2192.47  4684.1 2193.89
    4695 2189.96  4698.9  2190.2  4713.6 2183.42  4778.8 2169.72  4814.5  2163.7
  4855.6 2160.22    4871 2158.29  4885.8 2159.59  4906.7 2154.75  4915.3 2154.91
  4921.4 2151.72    4951 2146.14  4973.7 2136.24  4974.2 2135.74  4982.3 2136.24
  4992.8 2143.97  5020.2 2146.61  5022.4 2150.68  5049.9 2167.41    5060 2170.39
  5239.8  2175.6  5267.7 2178.79  5298.1 2186.48  5325.2 2188.68  5461.3 2190.63
#Mann= 8 ,-1 , 0
  4466.2    .035       0  4519.3     .07       0  4641.5    .035       0
    4695     .07       0  4855.6     .16       0  4973.7     .07       0
  4982.3     .16       0    5060     .07       0
Bank Sta=4973.7,4982.3
XS Rating Curve= 0 ,0
Exp/Cntr=0.3,0.1

Type RM Length L Ch R = 1 ,22274   ,147,147,147
BEGIN DESCRIPTION:
683
END DESCRIPTION:
XS GIS Cut Line= 3
      1530885.73       6788939.4      1530560.23      6788644.28
       1530004.7      6788383.88
#Sta/Elev= 30
  4548.6 2204.31  4663.3 2200.85  4705.9 2195.33  4755.2 2192.61  4770.2 2189.68
    4812 2172.96  4840.4 2164.63  4903.9 2157.15  4932.3 2150.93  4939.7 2147.97
    4988 2143.95  4995.1 2141.91  5004.8 2135.41  5013.6 2134.65  5014.1 2134.15
  5022.2 2134.65  5026.9 2141.29    5049 2150.99  5058.1 2153.01  5063.6 2156.07
  5080.9 2153.92  5093.1 2160.91  5104.7  2163.6  5115.2 2165.61  5177.7 2169.64
  5297.4  2172.3  5325.7 2175.94    5343 2180.38  5388.7 2188.37  5601.5 2189.88
#Mann= 5 ,-1 , 0
  4548.6     .07       0  4770.2     .16       0  5013.6     .07       0
  5022.2     .16       0  5104.7     .07       0
Bank Sta=5013.6,5022.2
XS Rating Curve= 0 ,0
Exp/Cntr=0.3,0.1

Type RM Length L Ch R = 1 ,22127   ,267,267,267
BEGIN DESCRIPTION:
682
END DESCRIPTION:
XS GIS Cut Line= 3
      1530933.47      6788817.87       1530599.3      6788509.73
      1530243.41      6788314.43
#Sta/Elev= 30
  4532.8 2201.36  4708.3 2198.21  4750.8 2192.89  4767.5  2186.6  4793.4 2178.09
  4800.7  2172.7  4850.1 2162.79  4892.6 2147.86  4984.5 2141.89  4986.9 2136.92
  5010.8  2133.7  5011.3  2133.2  5019.4  2133.7  5049.3 2155.83  5081.1 2169.06
  5086.9  2167.4  5130.5 2178.62  5146.5 2174.84  5168.3 2179.28  5184.4  2175.2
  5190.1 2178.68  5206.2 2176.42  5215.1 2178.92    5228 2177.56  5233.7 2181.75
  5249.8 2180.67  5255.5  2183.5  5287.7 2182.15  5331.3 2188.06  5393.3 2188.83
#Mann= 5 ,-1 , 0
  4532.8     .07       0  4767.5     .16       0  5010.8     .07       0
  5019.4     .16       0  5215.1     .07       0
Bank Sta=5010.8,5019.4
XS Rating Curve= 0 ,0
Exp/Cntr=0.3,0.1

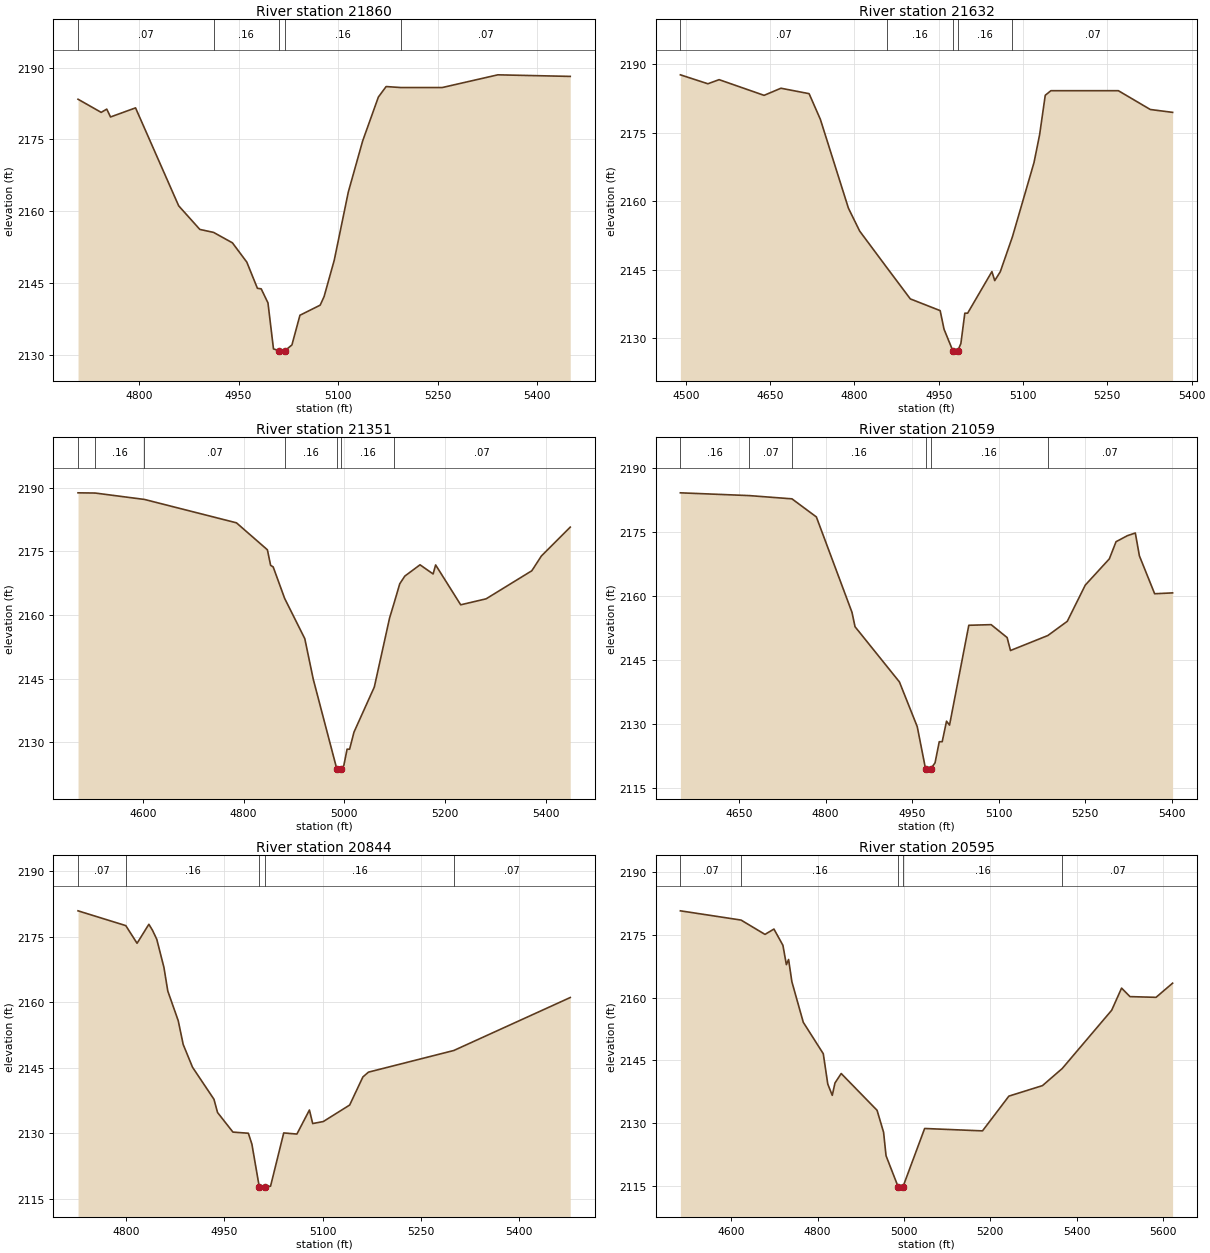
Type RM Length L Ch R = 1 ,21860   ,228,228,228
BEGIN DESCRIPTION:
681
END DESCRIPTION:
XS GIS Cut Line= 4
       1530825.4      6788110.52      1530568.43      6788254.63
      1530420.86      6788348.38      1530160.96      6788266.69
#Sta/Elev= 30
  4708.1 2183.39    4743 2180.64  4751.4 2181.32  4757.1 2179.68  4794.8 2181.58
  4859.8 2161.11  4891.7 2156.17  4912.4 2155.55  4940.8 2153.37  4962.5 2149.34
  4978.5 2143.86  4984.2 2143.75  4994.4 2140.81  5002.7  2131.2  5011.2 2130.81
  5011.7 2130.31  5019.9 2130.81  5030.5 2132.02  5042.6 2138.23  5073.1 2140.34
    5079 2142.14  5094.3 2149.74  5115.5 2163.99  5137.1 2174.66  5160.8 2183.84
  5172.5 2186.04  5194.5 2185.83    5257 2185.83  5340.9 2188.49    5450 2188.16
#Mann= 5 ,-1 , 0
  4708.1     .07       0  4912.4     .16       0  5011.2     .07       0
  5019.9     .16       0  5194.5     .07       0
Bank Sta=5011.2,5019.9
XS Rating Curve= 0 ,0
Exp/Cntr=0.3,0.1

Type RM Length L Ch R = 1 ,21632   ,281,281,281
BEGIN DESCRIPTION:
680
END DESCRIPTION:
XS GIS Cut Line= 3
      1530963.84      6788088.72      1530456.07      6788071.37
      1530088.57      6788084.34
#Sta/Elev= 30
  4490.3 2187.69  4539.2 2185.73  4559.2 2186.63  4639.2 2183.19  4669.2 2184.75
  4719.3 2183.56  4739.3 2177.95  4789.3 2158.45  4809.3 2153.43  4857.5 2145.45
  4899.4 2138.56  4952.5 2135.99  4959.4 2131.92  4975.1 2127.17  4975.6 2126.67
  4983.8 2127.17  4989.4 2128.79  4996.4 2135.43  5001.4 2135.43  5044.6 2144.55
  5049.6 2142.57  5059.5 2144.52  5081.1 2152.18  5119.5 2168.46  5129.5 2174.58
  5139.5  2183.2  5149.5 2184.21  5269.6 2184.21  5326.4 2180.09  5366.1 2179.46
#Mann= 5 ,-1 , 0
  4490.3     .07       0  4857.5     .16       0  4975.1     .07       0
  4983.8     .16       0  5081.1     .07       0
Bank Sta=4975.1,4983.8
XS Rating Curve= 0 ,0
Exp/Cntr=0.3,0.1

Type RM Length L Ch R = 1 ,21351   ,292,292,292
BEGIN DESCRIPTION:
679
END DESCRIPTION:
XS GIS Cut Line= 3
       1531076.7      6787902.09      1530547.21      6787819.63
      1530109.46      6787880.31
#Sta/Elev= 30
    4471 2188.83    4505 2188.78    4603 2187.27  4785.7 2181.76  4847.2  2175.4
  4853.6 2171.74  4858.7 2171.36  4881.5 2163.93  4921.5 2154.44  4938.3 2144.89
  4985.1 2123.72  4985.6 2123.22  4993.8 2123.72    4999 2124.54  5005.5 2128.39
  5010.5 2128.39  5019.2 2132.41  5059.6 2143.05  5089.9 2159.31    5099 2162.89
  5110.1 2167.38  5120.2  2169.2  5150.4 2171.86  5176.4  2169.7  5181.4 2171.83
  5231.2 2162.43  5281.7 2163.84  5372.5 2170.46  5391.6 2173.96  5448.8 2180.75
#Mann= 7 ,-1 , 0
    4471     .07       0    4505     .16       0    4603     .07       0
  4881.5     .16       0  4985.1     .07       0  4993.8     .16       0
    5099     .07       0
Bank Sta=4985.1,4993.8
XS Rating Curve= 0 ,0
Exp/Cntr=0.3,0.1

Type RM Length L Ch R = 1 ,21059   ,215,215,215
BEGIN DESCRIPTION:
678
END DESCRIPTION:
XS GIS Cut Line= 3
      1530994.26        6787633.      1530555.89      6787528.83
       1530169.8      6787641.62
#Sta/Elev= 30
  4548.5 2184.19  4667.8 2183.54  4741.8 2182.78  4784.1 2178.53  4845.8 2156.15
  4851.1 2152.77    4928 2139.82  4958.9 2129.31  4973.3 2119.39  4973.8 2118.89
    4982 2119.39  4989.7 2120.83    4997 2125.79  5002.1 2125.79  5009.6 2130.61
  5014.8 2129.69  5048.2 2153.11  5086.9 2153.26  5114.6 2150.23  5120.4 2147.19
  5185.2 2150.71  5218.8 2154.04    5250 2162.54  5291.7  2168.7  5303.3 2172.72
    5323 2174.14  5336.7 2174.76  5343.8 2169.39  5370.2 2160.51  5401.3 2160.71
#Mann= 6 ,-1 , 0
  4548.5     .16       0  4667.8     .07       0  4741.8     .16       0
  4973.3     .07       0    4982     .16       0  5185.2     .07       0
Bank Sta=4973.3,4982
XS Rating Curve= 0 ,0
Exp/Cntr=0.3,0.1

Type RM Length L Ch R = 1 ,20844   ,249,249,249
BEGIN DESCRIPTION:
677
END DESCRIPTION:
XS GIS Cut Line= 3
      1530855.33      6787437.66      1530594.96      6787324.84
      1530130.53      6787376.92
#Sta/Elev= 30
  4726.8 2180.94  4799.7 2177.55  4816.9  2173.5  4834.9 2177.86  4840.4  2176.5
    4847  2174.4  4857.9 2167.97  4863.8 2162.55  4879.7 2155.76  4887.3 2150.31
  4901.5  2145.1  4934.2 2137.76  4939.7 2134.72  4963.2 2130.23  4986.7 2129.97
  4992.1 2127.49  5003.4 2117.66  5003.9 2117.16  5012.2 2117.66  5020.6 2117.84
  5040.7 2130.04  5060.8 2129.78  5079.9 2135.29  5084.9 2132.19  5101.1 2132.65
  5141.3 2136.43  5161.5 2142.87    5170 2143.97  5300.2 2148.93  5477.9 2161.07
#Mann= 5 ,-1 , 0
  4726.8     .07       0  4799.7     .16       0  5003.4     .07       0
  5012.2     .16       0  5300.2     .07       0
Bank Sta=5003.4,5012.2
XS Rating Curve= 0 ,0
Exp/Cntr=0.3,0.1

Type RM Length L Ch R = 1 ,20595   ,262,262,262
BEGIN DESCRIPTION:
676
END DESCRIPTION:
XS GIS Cut Line= 3
      1531063.67      6786955.92      1530568.91       6787094.8
      1529983.01      6787316.14
#Sta/Elev= 30
    4482 2180.64  4622.5 2178.44    4678 2175.03  4698.7  2176.3  4719.5 2172.43
  4727.5 2167.82  4732.6 2169.06  4740.3 2163.74  4766.7 2154.09    4813 2146.61
  4823.4  2139.4  4833.8  2136.7  4840.1 2139.65  4854.5  2141.9  4937.6 2133.14
  4952.7  2127.9  4958.4 2122.32  4986.6 2114.87  4987.1 2114.37  4997.4 2114.87
  5047.8 2128.81  5181.8 2128.24    5243 2136.52  5320.8 2139.02  5366.6  2143.1
  5481.1 2156.97    5504 2162.24  5523.5 2160.21  5583.8 2160.04  5622.2 2163.41
#Mann= 5 ,-1 , 0
    4482     .07       0  4622.5     .16       0  4986.6     .07       0
  4997.4     .16       0  5366.6     .07       0
Bank Sta=4986.6,4997.4
XS Rating Curve= 0 ,0
Exp/Cntr=0.3,0.1

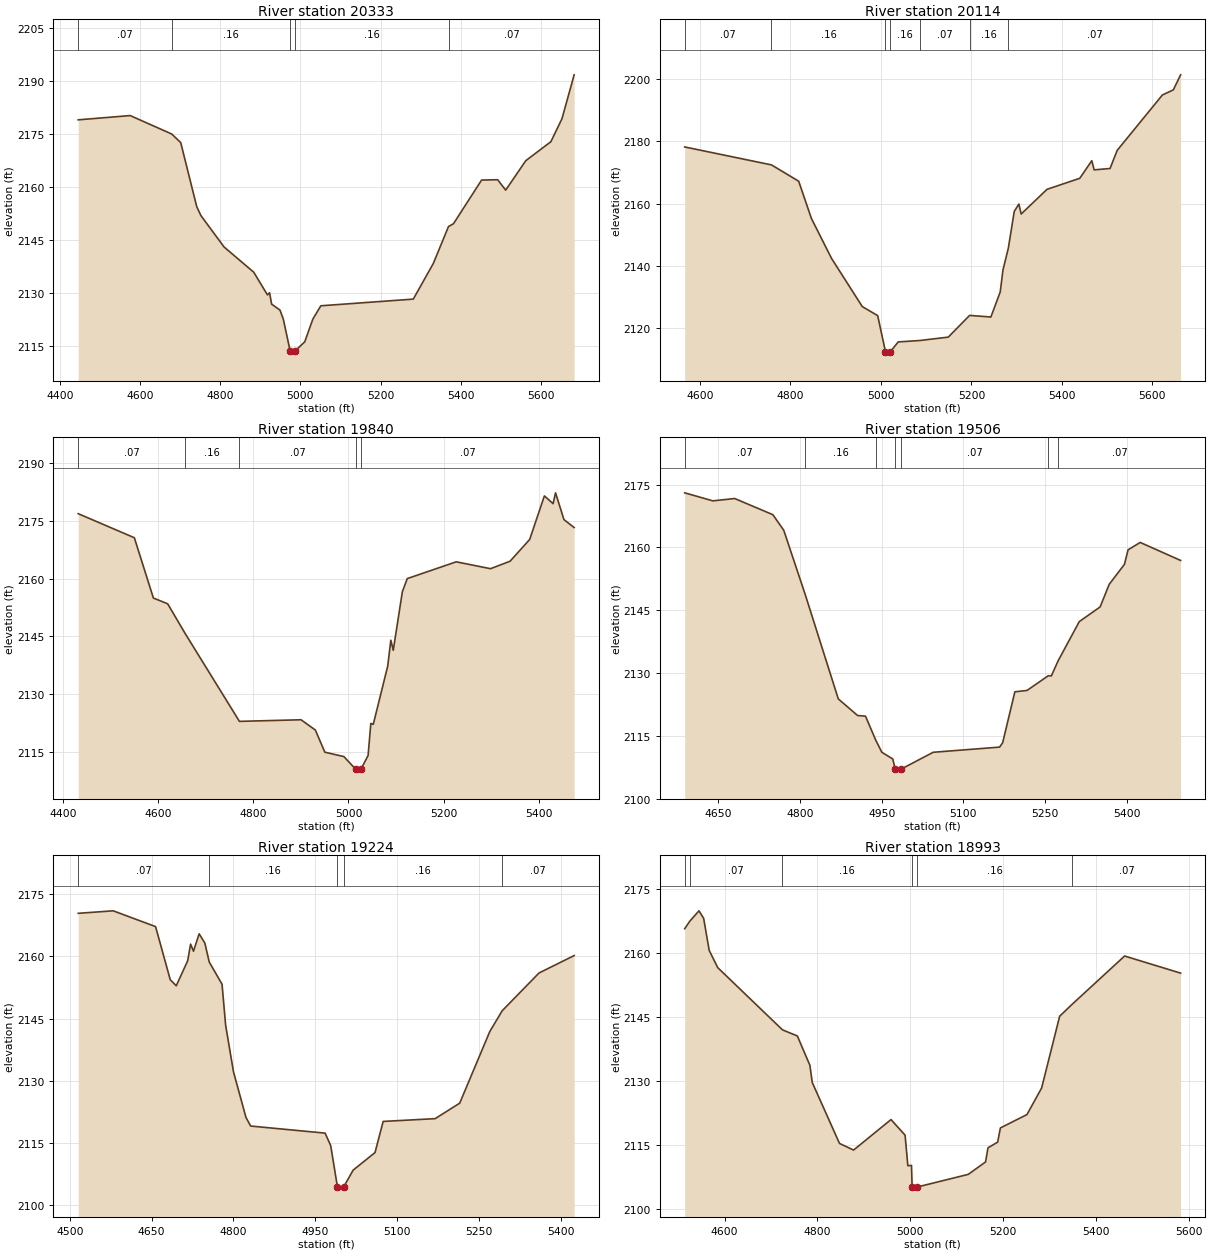
Type RM Length L Ch R = 1 ,20333   ,219,219,219
BEGIN DESCRIPTION:
675
END DESCRIPTION:
XS GIS Cut Line= 3
      1530989.89      6786725.89      1530456.07      6786873.45
      1529774.69      6786916.85
#Sta/Elev= 30
    4446 2179.02  4575.6 2180.23  4679.1 2175.01  4701.6 2172.58  4741.6 2154.41
    4752 2151.89  4809.8    2143  4883.6 2135.87  4917.9 2129.43  4923.1 2130.04
  4928.3 2126.82  4949.1 2125.13  4957.4 2122.57  4974.7 2113.44  4975.2 2112.94
  4985.8 2113.44  5010.9 2116.15    5031 2122.56    5051 2126.35  5281.5 2128.24
  5331.6 2138.37  5369.3  2148.8  5381.7 2149.59  5451.8 2161.96  5491.9 2162.06
  5511.9 2159.11    5562 2167.45  5624.6 2172.83  5652.2 2179.33  5682.6 2191.77
#Mann= 5 ,-1 , 0
    4446     .07       0  4679.1     .16       0  4974.7     .07       0
  4985.8     .16       0  5369.3     .07       0
Bank Sta=4974.7,4985.8
XS Rating Curve= 0 ,0
Exp/Cntr=0.3,0.1

Type RM Length L Ch R = 1 ,20114   ,274,274,274
BEGIN DESCRIPTION:
674
END DESCRIPTION:
XS GIS Cut Line= 3
       1530807.6      6786556.62      1530390.96       6786673.8
      1529749.46      6786842.84
#Sta/Elev= 30
  4566.2 2178.21  4758.1 2172.45  4818.2 2167.22  4846.3 2155.28  4890.9 2142.44
  4958.8 2127.01  4992.8 2124.11    5010 2112.58  5010.5 2112.08  5021.1 2112.58
  5038.2 2115.68  5085.5 2116.12  5148.8 2117.21    5196 2124.18    5243 2123.66
  5263.7 2131.71  5269.7 2138.71  5281.6 2145.75  5294.7 2157.54  5304.9 2159.89
    5310  2156.7  5367.1 2164.62  5439.5 2168.15  5466.1  2173.8  5471.3 2170.86
  5506.4  2171.3  5522.2 2177.11  5622.1 2194.87  5646.3 2196.52  5662.4 2201.34
#Mann= 7 ,-1 , 0
  4566.2     .07       0  4758.1     .16       0    5010     .07       0
  5021.1     .16       0  5085.5     .07       0    5196     .16       0
  5281.6     .07       0
Bank Sta=5010,5021.1
XS Rating Curve= 0 ,0
Exp/Cntr=0.3,0.1

Type RM Length L Ch R = 1 ,19840   ,334,334,334
BEGIN DESCRIPTION:
673
END DESCRIPTION:
XS GIS Cut Line= 3
      1530772.91      6786482.82      1530195.65      6786474.14
      1529744.23      6786582.66
#Sta/Elev= 30
  4432.4 2176.92  4550.3 2170.67  4590.3 2154.99  4620.3  2153.5  4657.1 2145.76
    4771 2122.94  4900.4 2123.36  4930.4  2120.7  4950.4 2114.93  4990.4 2113.79
  5015.1 2110.51  5015.6 2110.01  5026.2 2110.51  5041.2 2114.06    5047 2122.41
  5052.1 2122.16  5082.4 2137.29    5089 2144.03  5094.1 2141.42  5113.2 2156.64
  5123.5 2160.05  5226.4 2164.41  5298.4 2162.62  5339.5 2164.57  5380.6 2170.22
  5411.5 2181.54  5429.8 2179.52  5434.9 2182.34  5452.6 2175.38    5474 2173.32
#Mann= 5 ,-1 , 0
  4432.4     .07       0  4657.1     .16       0    4771     .07       0
  5015.1     .07       0  5026.2     .07       0
Bank Sta=5015.1,5026.2
XS Rating Curve= 0 ,0
Exp/Cntr=0.3,0.1

Type RM Length L Ch R = 1 ,19506   ,282,282,282
BEGIN DESCRIPTION:
672
END DESCRIPTION:
XS GIS Cut Line= 3
      1530846.71      6786239.77      1530430.02      6786257.13
      1529988.67      6786036.45
#Sta/Elev= 30
  4588.4 2173.03  4640.2 2171.11  4680.2 2171.67  4750.3 2167.81  4770.3 2164.09
  4809.8  2148.7  4870.4 2123.81  4905.8 2119.84  4920.4 2119.68  4938.9 2114.04
  4950.4 2111.05  4970.4 2109.46  4974.9 2107.05  4975.4 2106.55  4986.1 2107.05
  5044.6 2111.05  5166.6 2112.29  5172.2 2113.34  5194.6  2125.5  5216.9 2125.82
    5256 2129.34  5261.6 2129.29  5273.9 2132.87  5312.9 2142.27  5351.1 2145.77
  5367.9 2151.19  5395.8 2155.95  5402.4 2159.41  5424.7 2161.18  5498.9 2156.88
#Mann= 7 ,-1 , 0
  4588.4     .07       0  4809.8     .16       0  4938.9     .07       0
  4974.9     .07       0  4986.1     .07       0    5256     .16       0
  5273.9     .07       0
Bank Sta=4974.9,4986.1
XS Rating Curve= 0 ,0
Exp/Cntr=0.3,0.1

Type RM Length L Ch R = 1 ,19224   ,231,231,231
BEGIN DESCRIPTION:
671
END DESCRIPTION:
XS GIS Cut Line= 3
      1530916.17      6786165.99      1530456.07      6786018.41
      1530030.74      6785988.03
#Sta/Elev= 30
  4515.4 2170.38  4579.6 2170.98  4657.3 2167.18  4684.2 2154.39  4695.2 2152.92
  4716.2 2158.96  4721.5 2162.96  4726.8 2161.25  4737.2 2165.44  4747.7  2163.2
  4755.7 2158.66  4779.2 2153.29  4785.8 2143.42  4800.2 2132.18  4823.1  2121.2
  4831.7 2119.13  4968.2 2117.42  4978.5 2114.42  4990.9 2104.43  4991.4 2103.93
  5002.1 2104.43  5019.7 2108.51  5059.8 2112.74  5074.7 2120.24  5170.1 2120.91
  5215.1 2124.64  5270.3  2141.9    5293  2146.9  5360.6 2156.01    5425  2160.2
#Mann= 5 ,-1 , 0
  4515.4     .07       0  4755.7     .16       0  4990.9     .07       0
  5002.1     .16       0    5293     .07       0
Bank Sta=4990.9,5002.1
XS Rating Curve= 0 ,0
Exp/Cntr=0.3,0.1

Type RM Length L Ch R = 1 ,18993   ,208,208,208
BEGIN DESCRIPTION:
670
END DESCRIPTION:
XS GIS Cut Line= 3
      1530985.56       6785736.3      1530508.15       6785801.4
      1529950.21      6785983.05
#Sta/Elev= 30
  4514.1 2165.64  4524.9 2167.38  4544.9 2169.84    4555 2168.08  4566.9 2160.58
  4585.3 2156.53  4724.8 2141.95  4756.9 2140.51  4783.9 2133.64    4789 2129.61
  4847.7 2115.33    4878 2113.77  4958.7 2120.92    4989 2117.27    4995 2110.11
  5002.8 2110.18  5004.2 2105.12  5004.7 2104.62  5015.4 2105.12  5125.2 2108.08
  5162.4 2110.99  5167.7 2114.31  5188.5 2115.63  5194.4 2118.96  5251.6 2122.09
  5283.2 2128.31  5322.1 2145.14  5348.8 2147.92    5462 2159.25  5582.7 2155.24
#Mann= 6 ,-1 , 0
  4514.1     .16       0  4524.9     .07       0  4724.8     .16       0
  5004.2     .07       0  5015.4     .16       0  5348.8     .07       0
Bank Sta=5004.2,5015.4
XS Rating Curve= 0 ,0
Exp/Cntr=0.3,0.1

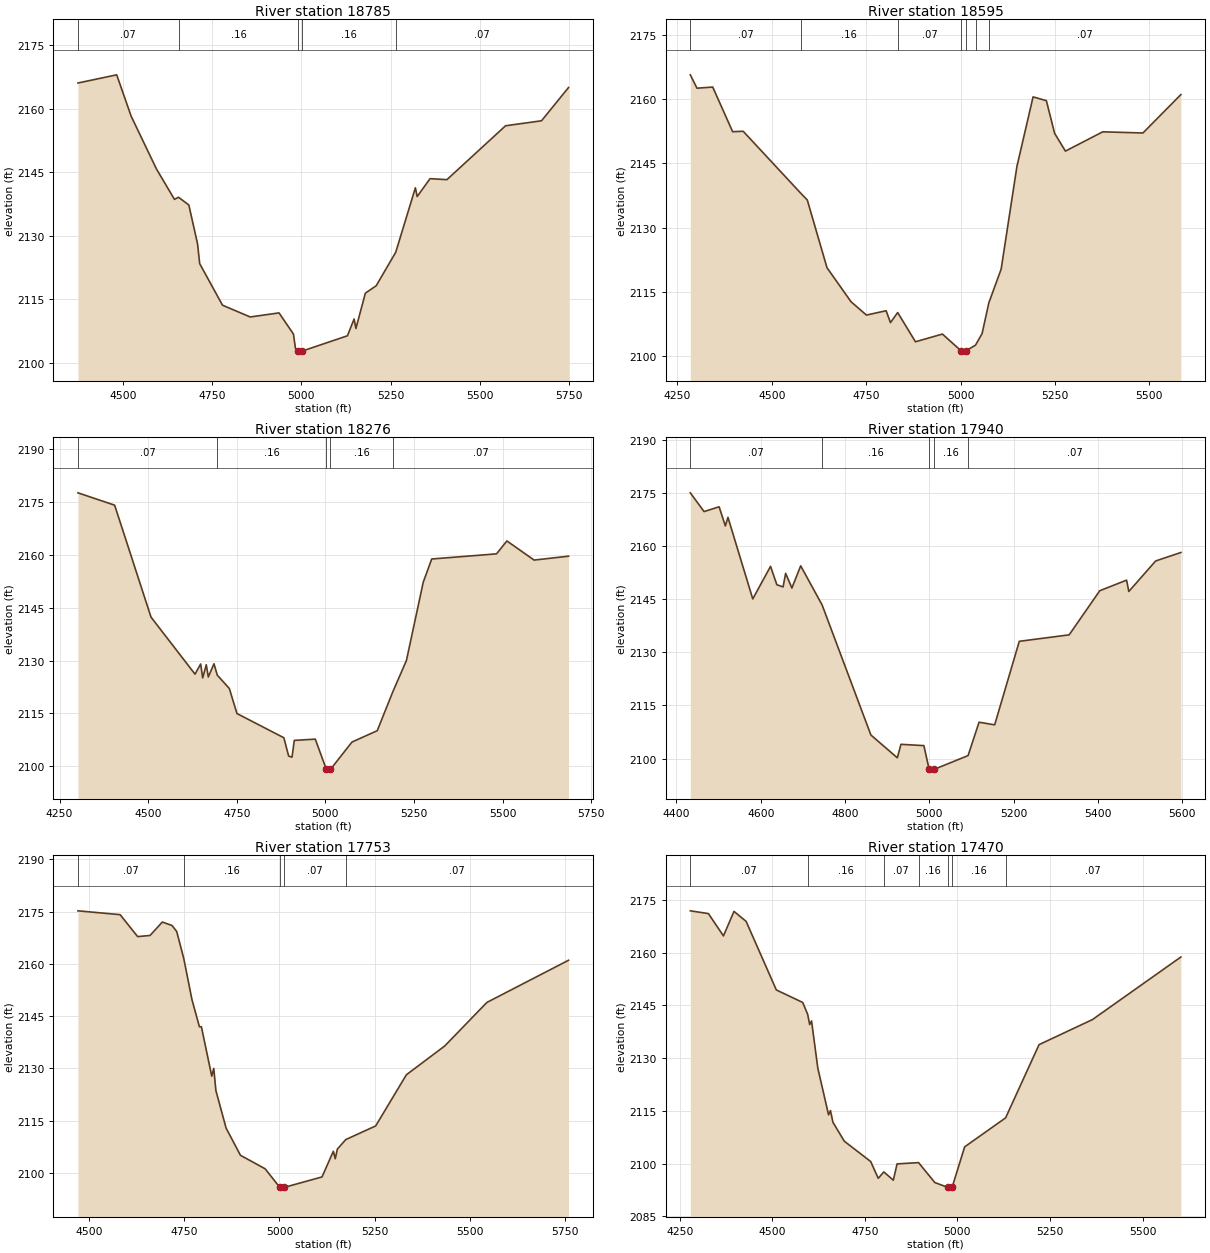
Type RM Length L Ch R = 1 ,18785   ,190,190,190
BEGIN DESCRIPTION:
669
END DESCRIPTION:
XS GIS Cut Line= 3
      1531072.43      6785701.58      1530451.73      6785610.43
      1529709.75      6785523.65
#Sta/Elev= 30
    4374 2166.03  4482.6 2167.96    4523 2158.22  4593.8 2145.78  4644.4 2138.58
  4655.9 2139.08  4684.7 2137.25  4709.2 2128.06  4715.1 2123.42    4779 2113.62
  4856.6 2110.84  4937.4  2111.8  4977.8 2106.81  4983.3 2103.48  4991.6 2102.81
  4992.1 2102.31  5002.8 2102.81    5129  2106.4  5147.7 2110.36  5152.8 2108.12
  5179.3 2116.46  5209.5 2118.19  5264.4 2126.11  5319.4 2141.31  5324.4 2139.24
  5360.5 2143.47  5407.7 2143.23    5572 2155.94  5672.8 2157.12  5748.4 2164.96
#Mann= 5 ,-1 , 0
    4374     .07       0  4655.9     .16       0  4991.6     .07       0
  5002.8     .16       0  5264.4     .07       0
Bank Sta=4991.6,5002.8
XS Rating Curve= 0 ,0
Exp/Cntr=0.3,0.1

Type RM Length L Ch R = 1 ,18595   ,319,319,319
BEGIN DESCRIPTION:
668
END DESCRIPTION:
XS GIS Cut Line= 3
      1531141.83      6785653.83      1530460.41      6785449.84
      1530013.35      6785067.89
#Sta/Elev= 30
  4284.2 2165.65  4301.8 2162.53  4343.5  2162.8  4396.3 2152.38  4424.2 2152.48
  4576.1 2138.08    4594 2136.44  4646.2 2120.64  4709.8 2112.71  4750.6 2109.59
  4802.8  2110.6  4814.3 2107.83  4833.4 2110.18  4880.5 2103.36  4951.9 2105.16
  5001.8 2101.21  5002.3 2100.71  5013.5 2101.21  5039.6 2102.58    5057 2105.27
  5074.8 2112.43  5107.5 2120.32  5149.2 2144.26    5192  2160.5  5227.2 2159.62
  5249.1 2151.99  5277.7 2147.85  5376.5 2152.35    5483 2152.08  5583.5 2161.04
#Mann= 7 ,-1 , 0
  4284.2     .07       0  4576.1     .16       0  4833.4     .07       0
  5001.8     .07       0  5013.5     .07       0  5039.6     .16       0
  5074.8     .07       0
Bank Sta=5001.8,5013.5
XS Rating Curve= 0 ,0
Exp/Cntr=0.3,0.1

Type RM Length L Ch R = 1 ,18276   ,336,336,336
BEGIN DESCRIPTION:
667
END DESCRIPTION:
XS GIS Cut Line= 3
      1531311.11      6785623.45      1530703.46      6785280.57
      1530069.85      6785015.84
#Sta/Elev= 30
  4301.8 2177.68  4405.4 2174.17    4508 2142.37  4632.2 2126.16  4648.1 2129.06
  4653.8  2125.1    4664 2128.85  4669.7 2125.36  4685.7 2129.11  4695.1 2125.87
    4729 2122.09  4750.6 2114.97  4882.9 2108.09  4896.5 2102.88  4905.9 2102.58
  4912.4 2107.34  4971.6  2107.7  5002.8 2099.11  5003.3 2098.61  5014.5 2099.11
  5075.1 2106.87  5146.5  2110.1  5189.9 2121.03  5228.8 2130.04  5276.4 2152.34
  5300.2 2158.88  5483.1 2160.34  5512.3 2164.01  5589.2 2158.57  5686.2 2159.68
#Mann= 5 ,-1 , 0
  4301.8     .07       0  4695.1     .16       0  5002.8     .07       0
  5014.5     .16       0  5189.9     .07       0
Bank Sta=5002.8,5014.5
XS Rating Curve= 0 ,0
Exp/Cntr=0.3,0.1

Type RM Length L Ch R = 1 ,17940   ,187,187,187
BEGIN DESCRIPTION:
666
END DESCRIPTION:
XS GIS Cut Line= 3
      1531376.19      6785402.08      1530924.82      6785085.25
      1530343.23      6784894.29
#Sta/Elev= 30
    4433 2175.11  4465.6 2169.81  4501.3 2171.16  4516.1 2165.76  4522.3 2168.18
  4581.1 2145.12  4623.3 2154.33  4638.2 2149.14    4653 2148.51  4659.1 2152.36
  4673.9  2148.2  4694.8 2154.47  4745.6 2143.42  4861.3 2106.66    4924 2100.22
  4932.7 2104.03    4987 2103.66  4999.5 2096.95    5000 2096.45  5011.2 2096.95
  5091.8 2100.84  5117.9 2110.28  5154.9 2109.53  5213.3 2133.14  5331.6 2134.97
  5404.2 2147.44  5467.8 2150.43  5473.1 2147.23  5536.7 2155.85  5596.6 2158.25
#Mann= 5 ,-1 , 0
    4433     .07       0  4745.6     .16       0  4999.5     .07       0
  5011.2     .16       0  5091.8     .07       0
Bank Sta=4999.5,5011.2
XS Rating Curve= 0 ,0
Exp/Cntr=0.3,0.1

Type RM Length L Ch R = 1 ,17753   ,283,283,283
BEGIN DESCRIPTION:
665
END DESCRIPTION:
XS GIS Cut Line= 3
      1531510.74      6785089.59       1530998.6        6784929.
      1530252.05       6784842.2
#Sta/Elev= 30
  4470.7 2175.25  4581.5 2174.15  4627.5 2167.85    4660 2168.18  4692.4 2172.03
  4717.8 2171.04  4730.1 2169.31  4748.5 2161.63  4770.2 2149.74  4789.7 2141.98
  4794.9 2141.98  4822.1  2127.8  4827.4 2130.01    4833 2123.65  4859.8 2112.89
  4897.5 2105.08  4962.3 2101.21  5000.8 2095.87  5001.3 2095.37  5012.5 2095.87
  5111.7 2098.87  5141.4 2106.23  5146.5 2104.09    5152 2106.87  5174.1 2109.59
  5252.7 2113.52  5333.2 2128.19  5433.9 2136.45  5544.6 2148.95    5759 2161.06
#Mann= 5 ,-1 , 0
  4470.7     .07       0  4748.5     .16       0  5000.8     .07       0
  5012.5     .07       0  5174.1     .07       0
Bank Sta=5000.8,5012.5
XS Rating Curve= 0 ,0
Exp/Cntr=0.3,0.1

Type RM Length L Ch R = 1 ,17470   ,158,158,158
BEGIN DESCRIPTION:
664
END DESCRIPTION:
XS GIS Cut Line= 3
      1531562.82      6784846.54      1530842.35      6784703.31
      1530252.07      6784685.95
#Sta/Elev= 30
  4278.5 2171.85  4327.3 2171.07    4368 2164.72  4396.4 2171.69  4429.2 2168.86
  4510.8 2149.37  4582.1 2145.81  4595.5 2142.43  4600.9 2139.52    4606 2140.56
  4622.9 2127.13    4652 2113.86  4657.1 2115.09  4663.7 2111.76  4694.3 2106.39
  4765.7 2100.61  4786.1 2095.83  4801.2 2097.65  4826.8  2095.3    4837 2099.93
    4895 2100.29    4939 2094.63  4973.9 2093.26  4974.4 2092.76  4985.6 2093.26
  5019.5 2104.77  5130.1 2113.01  5220.5 2133.82  5364.7 2140.94  5603.6 2158.73
#Mann= 7 ,-1 , 0
  4278.5     .07       0  4595.5     .16       0  4801.2     .07       0
    4895     .16       0  4973.9     .07       0  4985.6     .16       0
  5130.1     .07       0
Bank Sta=4973.9,4985.6
XS Rating Curve= 0 ,0
Exp/Cntr=0.3,0.1