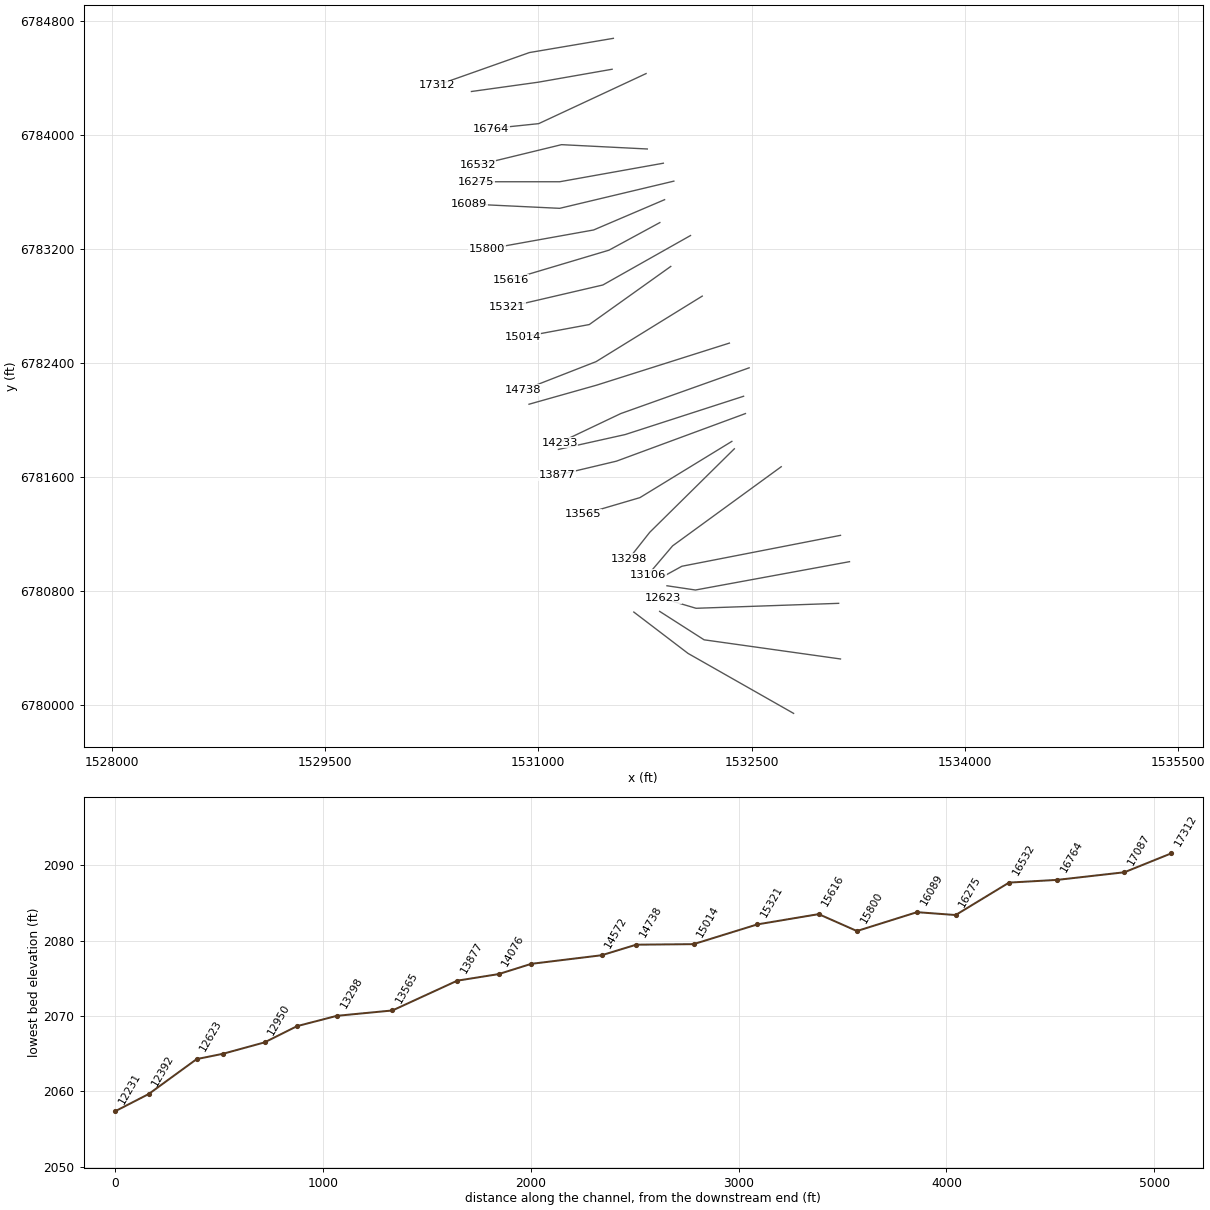
HEC-RAS study Elm 85.prj: Elm 85 Base Level Engineering

--- Elm 85.g01 (geometry) --- (continued)

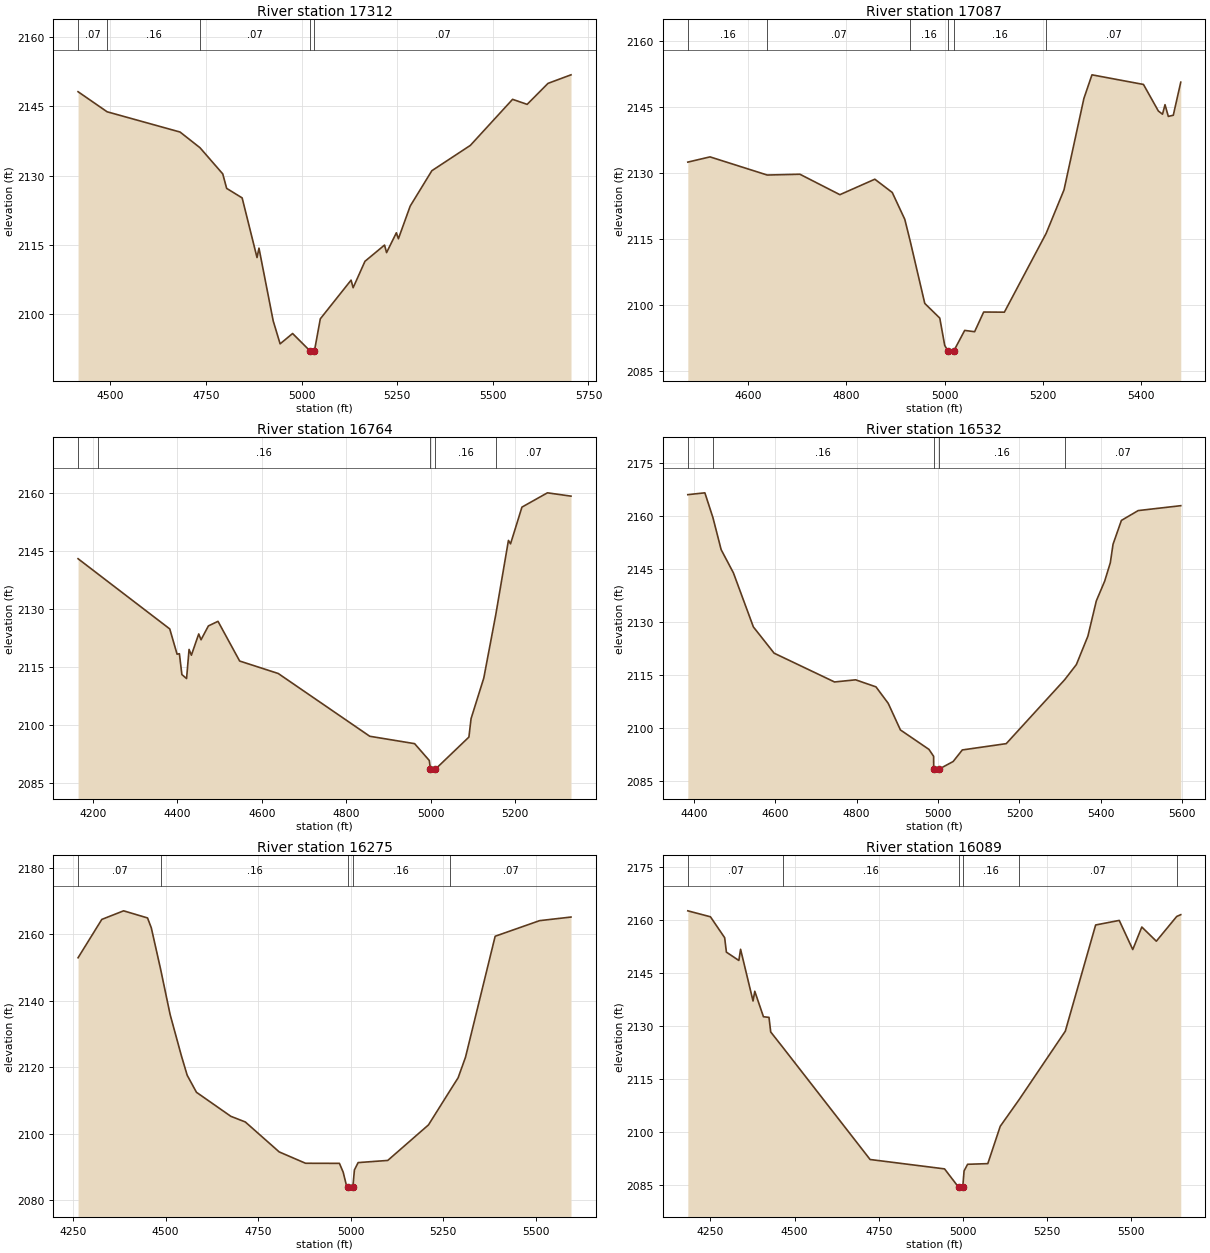
Type RM Length L Ch R = 1 ,17312   ,225,225,225
BEGIN DESCRIPTION:
663
END DESCRIPTION:
XS GIS Cut Line= 3
      1531528.11      6784681.61      1530937.84      6784581.78
      1530286.83      6784351.76
#Sta/Elev= 30
  4415.2  2148.2  4491.2 2143.85    4682 2139.46  4734.1 2136.06  4793.6 2130.39
  4803.8 2127.25  4844.3 2125.19  4883.2 2112.26  4888.3  2114.3  4925.5 2098.54
  4943.6 2093.56  4976.2  2095.8  5021.6 2092.05  5022.1 2091.55  5033.4 2092.05
  5048.7 2098.98  5129.2 2107.37  5134.5 2105.72  5165.5 2111.45  5216.7 2114.97
    5222 2113.33  5247.6 2117.63  5252.9 2116.33  5283.8 2123.42  5340.4 2131.08
  5441.1 2136.57  5551.5 2146.55  5589.6 2145.46  5644.2 2150.01  5704.3 2151.86
#Mann= 5 ,-1 , 0
  4415.2     .07       0  4491.2     .16       0  4734.1     .07       0
  5021.6     .07       0  5033.4     .07       0
Bank Sta=5021.6,5033.4
XS Rating Curve= 0 ,0
Exp/Cntr=0.3,0.1

Type RM Length L Ch R = 1 ,17087   ,323,323,323
BEGIN DESCRIPTION:
662
END DESCRIPTION:
XS GIS Cut Line= 3
      1531519.43      6784464.59       1530998.6      6784373.45
      1530529.94      6784308.36
#Sta/Elev= 30
  4478.2 2132.51  4523.3  2133.7  4639.6 2129.57    4706 2129.75  4787.3  2125.1
  4858.3 2128.62  4893.7  2125.6  4919.2 2119.49  4930.1 2114.57  4959.8 2100.36
  4990.3 2097.02  5000.4 2090.78    5007 2089.55  5007.5 2089.05  5018.8 2089.55
  5040.9 2094.22  5061.1 2093.92  5079.5  2098.4  5121.6 2098.37  5206.5  2116.3
  5242.8  2126.2  5283.2 2146.99  5299.6 2152.37  5404.3 2150.18  5434.6 2144.13
    5443 2143.41  5448.1 2145.58  5454.8 2142.91  5464.9 2143.17  5480.1  2150.7
#Mann= 6 ,-1 , 0
  4478.2     .16       0  4639.6     .07       0  4930.1     .16       0
    5007     .07       0  5018.8     .16       0  5206.5     .07       0
Bank Sta=5007,5018.8
XS Rating Curve= 0 ,0
Exp/Cntr=0.3,0.1

Type RM Length L Ch R = 1 ,16764   ,232,232,232
BEGIN DESCRIPTION:
661
END DESCRIPTION:
XS GIS Cut Line= 3
      1531758.15      6784434.21      1531002.94      6784082.65
      1530669.36      6784047.99
#Sta/Elev= 30
  4164.4    2143  4212.2    2139  4381.7 2124.84  4399.1  2118.3  4404.6 2118.42
  4410.5 2113.02  4421.6    2112  4427.5 2119.53    4433 2118.03  4450.4 2123.54
  4455.9 2122.03  4473.3 2125.61  4496.1  2126.8  4547.4 2116.53  4638.9  2113.3
  4855.8 2097.06  4962.1 2095.15    4997 2090.78  4999.5 2088.54    5000 2088.04
  5011.3 2088.54  5090.8 2096.85  5095.9 2101.61  5126.1 2112.14  5154.5 2128.53
  5184.5 2147.74  5189.5 2146.85  5216.5 2156.35  5276.9 2160.05  5332.8 2159.19
#Mann= 5 ,-1 , 0
  4164.4     .07       0  4212.2     .16       0  4999.5     .07       0
  5011.3     .16       0  5154.5     .07       0
Bank Sta=4999.5,5011.3
XS Rating Curve= 0 ,0
Exp/Cntr=0.3,0.1

Type RM Length L Ch R = 1 ,16532   ,257,257,257
BEGIN DESCRIPTION:
660
END DESCRIPTION:
XS GIS Cut Line= 3
      1531766.84       6783904.7      1531163.53      6783935.08
      1530573.24      6783791.85
#Sta/Elev= 30
    4385 2166.13  4426.9 2166.65  4446.7 2159.62  4466.9 2150.53    4497 2143.95
  4546.1  2128.6  4597.1 2121.15  4745.6 2112.98  4797.4 2113.59  4847.4 2111.59
  4877.5 2106.92  4907.5 2099.37  4977.6 2093.85  4989.1 2091.88  4989.3 2088.18
  4989.8 2087.68  5001.3 2088.18  5037.1 2090.41  5059.6 2093.69  5167.6 2095.48
  5311.2 2113.62  5339.9 2117.91  5368.3 2125.99  5388.9 2135.96  5409.5  2141.6
  5423.4 2146.82    5430 2152.04  5450.6 2158.82  5491.8 2161.61  5596.5    2163
#Mann= 5 ,-1 , 0
    4385     .07       0  4446.7     .16       0  4989.3     .07       0
  5001.3     .16       0  5311.2     .07       0
Bank Sta=4989.3,5001.3
XS Rating Curve= 0 ,0
Exp/Cntr=0.3,0.1

Type RM Length L Ch R = 1 ,16275   ,186,186,186
BEGIN DESCRIPTION:
659
END DESCRIPTION:
XS GIS Cut Line= 3
      1531879.67      6783804.87      1531150.51      6783674.66
      1530560.21      6783674.66
#Sta/Elev= 30
  4263.8 2152.89  4327.9 2164.41  4386.8 2166.99  4451.4 2164.85  4461.6 2161.86
  4486.6  2149.5  4512.3 2135.87  4542.8 2123.44  4558.5 2117.58  4583.5 2112.47
  4676.3 2105.26  4715.5 2103.55  4806.9 2094.56    4878 2091.15  4969.5 2091.12
  4979.6 2088.49  4989.8 2083.88  4993.7 2083.88  4994.2 2083.38  5005.7 2083.88
    5010 2089.14    5020 2091.35    5100    2092    5210 2102.68  5267.7 2112.91
    5290 2116.83    5310 2123.03    5390 2159.35    5510 2164.04  5594.8 2165.12
#Mann= 5 ,-1 , 0
  4263.8     .07       0  4486.6     .16       0  4993.7     .07       0
  5005.7     .16       0  5267.7     .07       0
Bank Sta=4993.7,5005.7
XS Rating Curve= 0 ,0
Exp/Cntr=0.3,0.1

Type RM Length L Ch R = 1 ,16089   ,289,289,289
BEGIN DESCRIPTION:
658
END DESCRIPTION:
XS GIS Cut Line= 3
      1531953.51      6783679.01      1531150.51      6783488.03
      1530512.53      6783518.41
#Sta/Elev= 30
  4183.1 2162.67  4250.3 2160.98  4292.5 2155.05  4297.7 2150.95  4334.7 2148.59
  4339.8 2151.76  4376.8 2137.11    4382 2139.86  4407.7 2132.64  4424.2 2132.46
  4429.3 2128.32  4465.3 2123.96  4724.5 2092.16  4945.6  2089.5  4987.6 2084.26
  4988.1 2083.76  4999.6 2084.26  5003.6 2088.92    5014  2090.8  5074.1 2090.99
    5111 2101.57  5167.9 2109.25  5304.3 2128.55  5394.4 2158.66  5464.5 2159.95
  5504.6 2151.69  5531.5 2158.08  5574.6 2154.06  5635.2 2161.08  5647.2 2161.58
#Mann= 6 ,-1 , 0
  4183.1     .07       0  4465.3     .16       0  4987.6     .07       0
  4999.6     .16       0  5167.9     .07       0  5635.2    .035       0
Bank Sta=4987.6,4999.6
XS Rating Curve= 0 ,0
Exp/Cntr=0.3,0.1

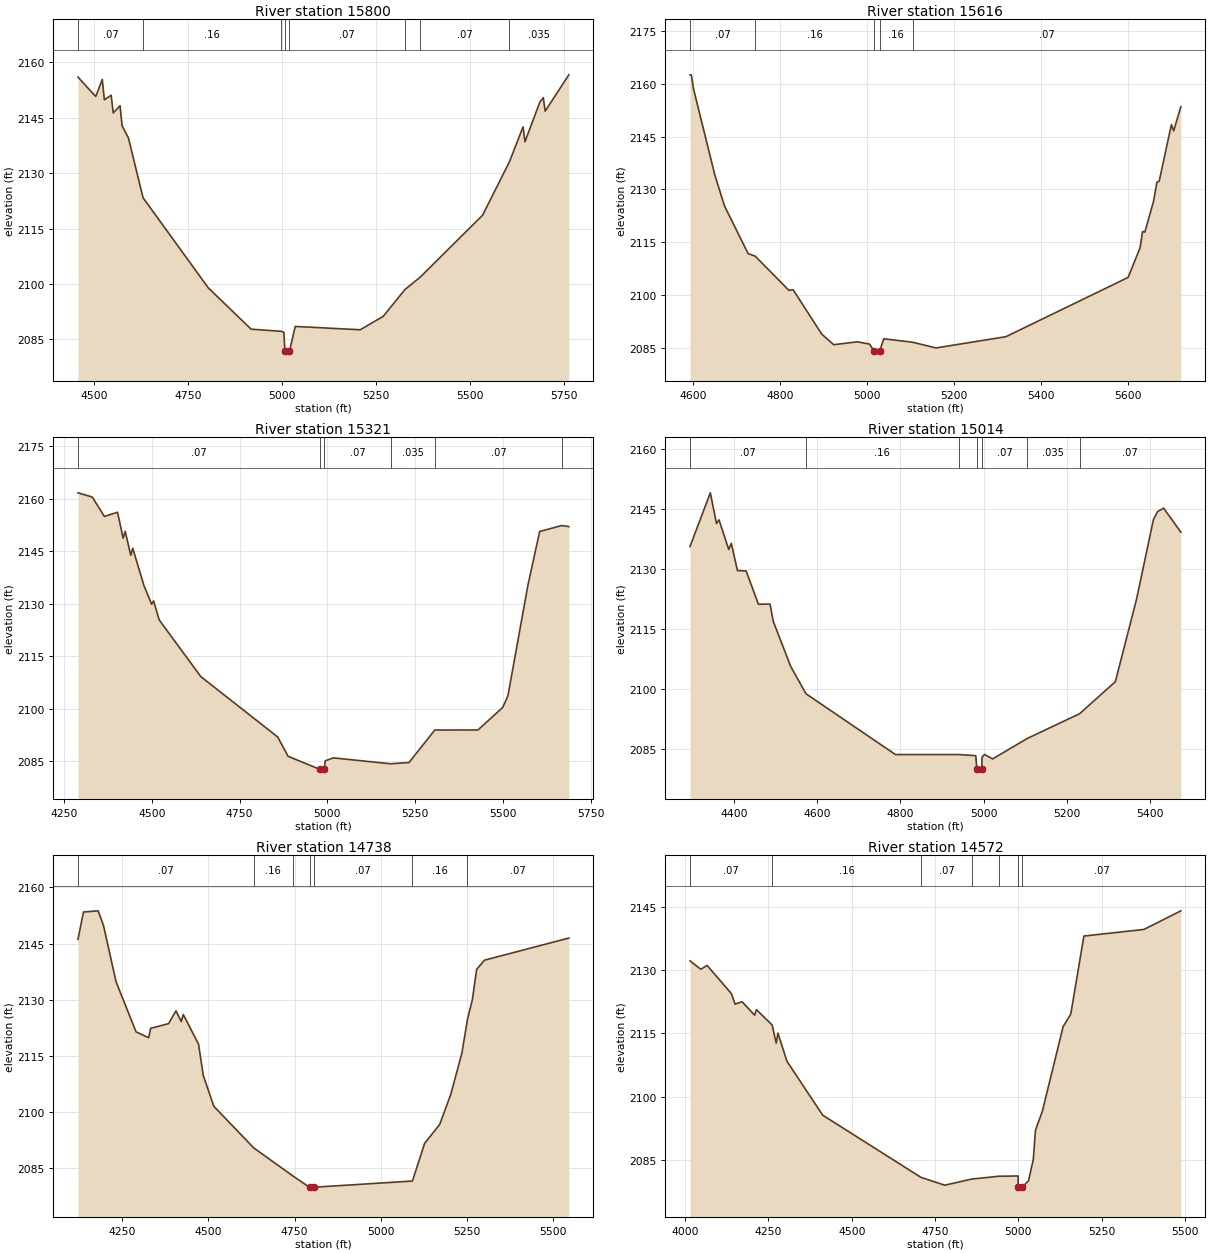
Type RM Length L Ch R = 1 ,15800   ,184,184,184
BEGIN DESCRIPTION:
657
END DESCRIPTION:
XS GIS Cut Line= 3
      1531888.38      6783548.81      1531389.23      6783336.12
      1530639.15      6783201.72
#Sta/Elev= 30
  4458.2 2156.04  4505.4 2150.79  4522.9 2155.41  4528.3  2149.9  4546.5 2151.13
  4551.9 2146.35  4570.1 2148.28  4575.5 2142.83  4592.3 2139.57  4631.2 2123.35
  4804.5 2098.95  4918.4 2087.75  4998.1 2087.17  5005.5 2086.92  5008.3 2081.76
  5008.8 2081.26  5020.3 2081.76  5035.6 2088.49  5208.3 2087.59  5269.2  2091.2
  5327.4 2098.51  5367.1 2101.78  5533.6 2118.63    5605 2133.11  5641.1 2142.56
  5646.2 2138.54  5685.7 2149.25  5694.8 2150.49  5699.9 2146.83  5762.8 2156.66
#Mann= 8 ,-1 , 0
  4458.2     .07       0  4631.2     .16       0  4998.1     .07       0
  5008.3     .07       0  5020.3     .07       0  5327.4     .16       0
  5367.1     .07       0    5605    .035       0
Bank Sta=5008.3,5020.3
XS Rating Curve= 0 ,0
Exp/Cntr=0.3,0.1

Type RM Length L Ch R = 1 ,15616   ,295,295,295
BEGIN DESCRIPTION:
14
END DESCRIPTION:
XS GIS Cut Line= 3
      1531855.01      6783388.01      1531496.86      6783194.04
      1530804.99        6782988.
#Sta/Elev= 30
  4592.7 2162.53  4595.6 2162.53  4600.8 2158.55  4650.2 2133.92  4672.3 2125.25
  4726.4 2111.77  4742.9 2111.02  4820.2 2101.33    4830  2101.5  4895.6 2088.93
  4923.2 2085.89  4977.4 2086.71  5005.4 2086.08  5016.8    2084  5017.3  2083.5
  5028.8    2084  5038.6 2087.57  5104.6  2086.6  5158.5 2084.97  5319.6 2088.17
  5600.6    2105    5628  2113.4  5633.8 2118.03    5639 2117.86  5659.3 2126.74
  5666.9 2132.07  5672.1 2132.34  5700.1  2148.4  5705.3 2146.62  5721.9 2153.48
#Mann= 5 ,-1 , 0
  4592.7     .07       0  4742.9     .16       0  5016.8     .07       0
  5028.8     .16       0  5104.6     .07       0
Bank Sta=5016.8,5028.8
XS Rating Curve= 0 ,0
Exp/Cntr=0.3,0.1

Type RM Length L Ch R = 1 ,15321   ,307,307,307
BEGIN DESCRIPTION:
656
END DESCRIPTION:
XS GIS Cut Line= 3
      1532070.63      6783297.05      1531454.33      6782949.84
      1530781.62      6782793.59
#Sta/Elev= 30
  4289.6 2161.73  4330.5 2160.53  4364.9 2154.97  4402.4 2156.18  4418.3 2148.73
  4424.1 2150.73    4440 2143.88  4445.7 2145.86  4477.6  2135.2  4499.3 2129.89
    4505 2130.81  4520.9  2125.4  4639.4 2109.18  4858.5  2091.9  4887.9 2086.39
  4978.7 2082.64  4979.2 2082.14  4990.7 2082.64  4993.8 2085.08  5016.8 2085.93
  5180.1 2084.24  5232.4  2084.6  5305.9  2093.9  5428.8 2093.91  5499.3 2100.36
  5514.1 2103.68  5571.2 2135.39  5604.5 2150.67  5667.6 2152.38  5687.6 2152.07
#Mann= 6 ,-1 , 0
  4289.6     .07       0  4978.7     .07       0  4990.7     .07       0
  5180.1    .035       0  5305.9     .07       0  5667.6    .035       0
Bank Sta=4978.7,4990.7
XS Rating Curve= 0 ,0
Exp/Cntr=0.3,0.1

Type RM Length L Ch R = 1 ,15014   ,276,276,276
BEGIN DESCRIPTION:
655
END DESCRIPTION:
XS GIS Cut Line= 3
      1531931.75      6783080.04      1531358.84      6782672.06
      1530890.13      6782585.26
#Sta/Elev= 30
    4294 2135.61  4342.9 2149.03  4357.7 2141.39  4363.8 2142.27  4387.2 2134.87
  4393.3 2136.41  4408.1 2129.61    4429 2129.52  4458.5 2121.19  4486.4 2121.25
  4494.2 2116.92    4536  2105.7  4572.8 2098.85    4788 2083.66  4940.1 2083.66
    4981 2083.38  4983.6 2080.02  4984.1 2079.52  4995.7 2080.02  4995.8 2082.91
  5001.8 2083.69  5021.6 2082.57  5104.6 2087.67  5230.4 2093.85  5316.5 2101.85
  5367.4 2122.43    5408 2142.33  5418.2 2144.36  5432.5 2145.21    5474  2139.2
#Mann= 7 ,-1 , 0
    4294     .07       0  4572.8     .16       0  4940.1     .07       0
  4983.6     .07       0  4995.7     .07       0  5104.6    .035       0
  5230.4     .07       0
Bank Sta=4983.6,4995.7
XS Rating Curve= 0 ,0
Exp/Cntr=0.3,0.1

Type RM Length L Ch R = 1 ,14738   ,166,166,166
BEGIN DESCRIPTION:
654
END DESCRIPTION:
XS GIS Cut Line= 3
      1532153.09       6782871.7      1531406.59      6782411.64
      1530895.71      6782212.49
#Sta/Elev= 30
  4121.1  2146.1  4137.1  2153.4  4179.6 2153.72    4195  2149.9  4231.7 2134.81
  4289.7 2121.43  4326.3 2119.85  4332.2 2122.36  4384.3 2123.62  4405.6 2127.04
    4421 2124.18  4426.9 2126.05  4471.2 2118.13  4484.8 2109.83  4515.6 2101.55
  4631.5 2090.45  4745.1 2082.97  4793.4 2079.95  4793.9 2079.45  4805.7 2079.95
  5092.2 2081.61  5127.5 2091.65  5171.4 2096.72  5203.6 2104.76  5235.8 2115.76
    5252 2124.75  5266.1 2129.96  5278.7  2138.1  5301.3 2140.55  5546.3 2146.45
#Mann= 7 ,-1 , 0
  4121.1     .07       0  4631.5     .16       0  4745.1     .07       0
  4793.4     .07       0  4805.7     .07       0  5092.2     .16       0
    5252     .07       0
Bank Sta=4793.4,4805.7
XS Rating Curve= 0 ,0
Exp/Cntr=0.3,0.1

Type RM Length L Ch R = 1 ,14572   ,339,339,339
BEGIN DESCRIPTION:
653
END DESCRIPTION:
XS GIS Cut Line= 3
      1532344.04      6782541.84      1531410.93      6782246.71
      1530934.94      6782112.57
#Sta/Elev= 30
  4014.5 2132.14    4047 2130.15  4065.9 2131.07  4138.7 2124.39  4149.8 2121.89
  4170.8 2122.46  4208.6 2119.27  4213.8 2120.58    4261 2116.96  4273.2 2112.67
  4278.4 2115.02  4305.5 2108.35  4412.9 2095.57  4707.7 2080.84  4779.1 2078.98
  4861.1 2080.45  4940.9  2081.1  4999.3 2081.17  4999.5 2078.55    5000 2078.05
  5011.8 2078.55  5030.5 2080.03  5044.9 2085.12  5051.3 2092.01  5072.1 2096.53
  5134.4 2116.57  5157.3 2119.53  5196.7 2138.02    5377 2139.59  5487.7    2144
#Mann= 7 ,-1 , 0
  4014.5     .07       0    4261     .16       0  4707.7     .07       0
  4861.1     .16       0  4940.9     .07       0  4999.5     .07       0
  5011.8     .07       0
Bank Sta=4999.5,5011.8
XS Rating Curve= 0 ,0
Exp/Cntr=0.3,0.1

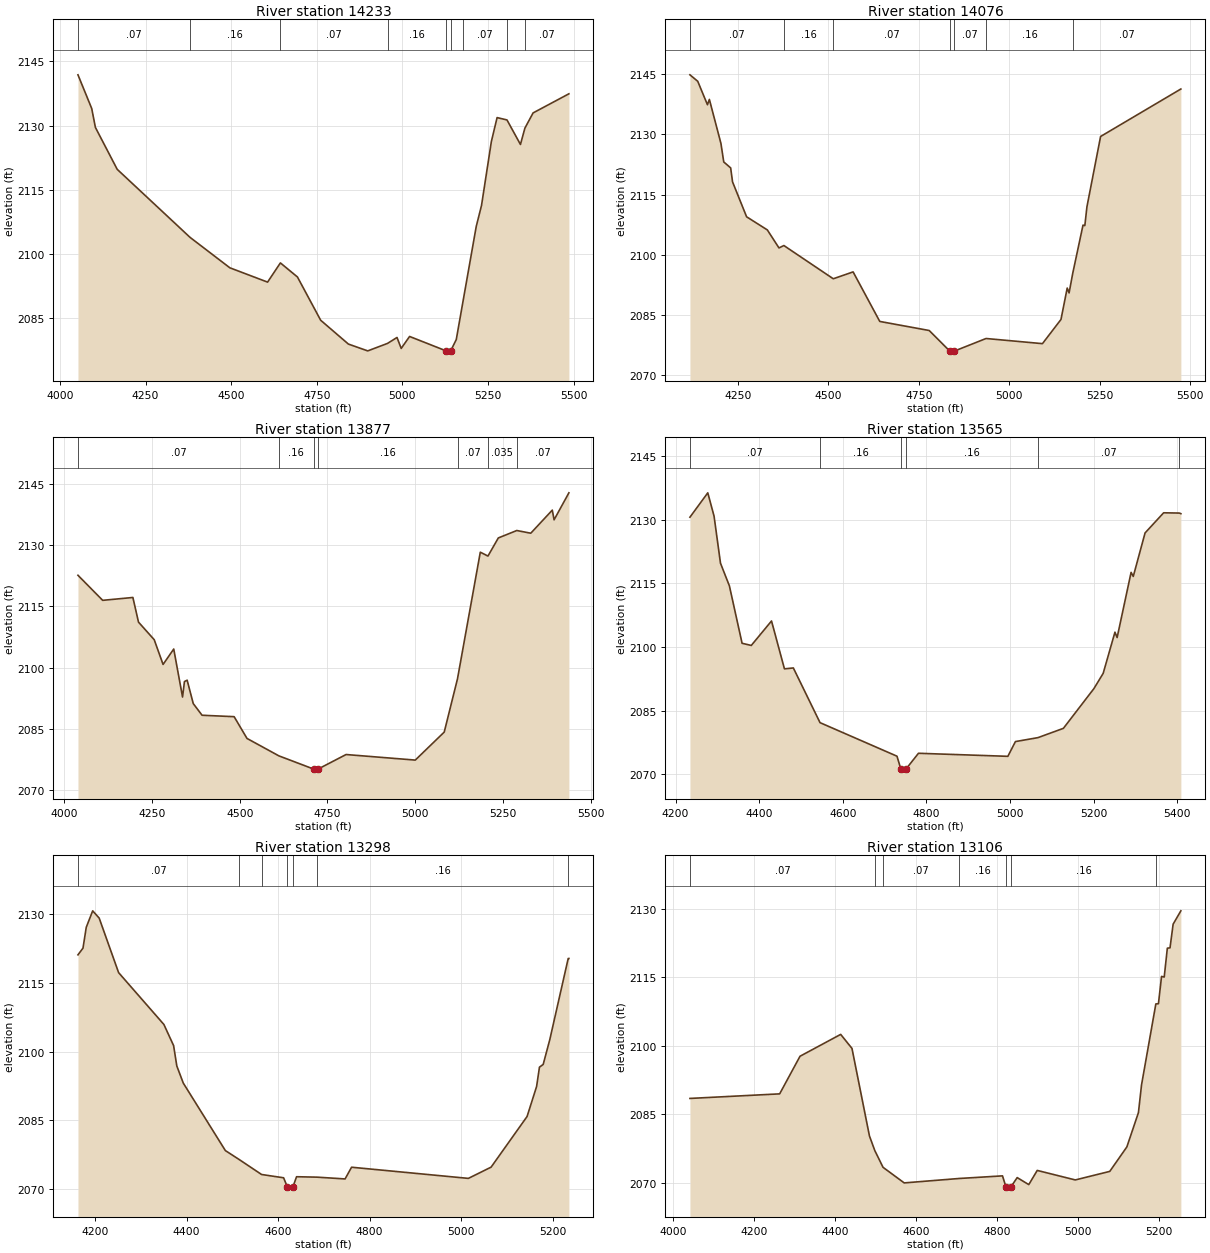
Type RM Length L Ch R = 1 ,14233   ,157,157,157
BEGIN DESCRIPTION:
652
END DESCRIPTION:
XS GIS Cut Line= 3
      1532482.93      6782368.22       1531580.2      6782047.06
      1531150.52      6781843.07
#Sta/Elev= 30
  4052.5 2141.85  4092.7 2133.99  4103.4 2129.58  4167.1  2119.8    4380 2103.91
  4496.1 2096.82  4606.3 2093.48  4643.7 2097.96  4693.5 2094.68  4761.4 2084.58
  4842.4 2079.02  4898.8 2077.43  4956.6 2079.18  4984.3 2080.56  4996.6 2078.01
    5021  2080.8  5128.5 2077.41    5129 2076.91  5140.9 2077.41  5157.4 2080.08
  5176.9 2088.92  5215.7 2106.47  5231.1 2111.37  5259.9  2126.3  5276.6 2131.87
  5305.5 2131.32  5344.8  2125.6  5357.8 2129.41  5381.7 2132.96  5486.3 2137.42
#Mann= 9 ,-1 , 0
  4052.5     .07       0    4380     .16       0  4643.7     .07       0
  4956.6     .16       0  5128.5     .07       0  5140.9     .16       0
  5176.9     .07       0  5305.5     .16       0  5357.8     .07       0
Bank Sta=5128.5,5140.9
XS Rating Curve= 0 ,0
Exp/Cntr=0.3,0.1

Type RM Length L Ch R = 1 ,14076   ,199,199,199
BEGIN DESCRIPTION:
651
END DESCRIPTION:
XS GIS Cut Line= 3
      1532443.89      6782168.58      1531610.58      6781899.49
      1531141.79      6781795.32
#Sta/Elev= 30
  4117.9 2144.83  4139.5 2143.22  4166.3 2137.38  4171.6 2138.71  4203.6 2127.73
  4211.3 2123.14  4230.4 2121.66  4235.6 2118.18  4274.4 2109.49  4331.7 2106.22
  4363.8 2101.74  4377.4 2102.33  4513.8 2094.06  4568.6 2095.77  4642.2 2083.44
  4778.8 2081.18  4835.6 2076.05  4836.1 2075.55    4848 2076.05  4935.7 2079.19
  5091.5 2077.91  5142.7 2083.93  5159.9 2091.75  5165.1 2090.54  5175.2 2095.43
  5203.5 2107.41  5208.6  2107.3  5214.4 2111.99  5252.1 2129.48  5473.8  2141.3
#Mann= 7 ,-1 , 0
  4117.9     .07       0  4377.4     .16       0  4513.8     .07       0
  4835.6     .07       0    4848     .07       0  4935.7     .16       0
  5175.2     .07       0
Bank Sta=4835.6,4848
XS Rating Curve= 0 ,0
Exp/Cntr=0.3,0.1

Type RM Length L Ch R = 1 ,13877   ,312,312,312
BEGIN DESCRIPTION:
650
END DESCRIPTION:
XS GIS Cut Line= 3
      1532456.91      6782047.05      1531549.82      6781712.86
      1531129.37      6781613.16
#Sta/Elev= 30
  4039.1 2122.59  4109.5 2116.46  4195.6 2117.16  4211.6 2111.13  4256.4 2106.83
  4281.6 2100.78    4312 2104.55  4337.1 2092.81  4342.5 2096.59  4350.2 2096.93
  4367.6  2091.2  4392.7 2088.35  4484.1    2088  4520.7 2082.68  4611.4 2078.42
  4710.8 2075.18  4711.3 2074.68  4723.2 2075.18    4803 2078.74  5000.2 2077.38
  5082.7 2084.23  5120.5 2097.27  5185.5 2128.24  5207.3 2127.29  5236.8 2131.72
  5289.4 2133.54  5329.3 2132.88  5390.6 2138.53  5395.7 2136.16  5437.9 2142.76
#Mann= 7 ,-1 , 0
  4039.1     .07       0  4611.4     .16       0  4710.8     .07       0
  4723.2     .16       0  5120.5     .07       0  5207.3    .035       0
  5289.4     .07       0
Bank Sta=4710.8,4723.2
XS Rating Curve= 0 ,0
Exp/Cntr=0.3,0.1

Type RM Length L Ch R = 1 ,13565   ,267,267,267
BEGIN DESCRIPTION:
649
END DESCRIPTION:
XS GIS Cut Line= 3
      1532361.41      6781851.73      1531714.75      6781456.78
      1531315.42      6781339.59
#Sta/Elev= 30
  4234.5 2130.61  4277.2 2136.36  4292.2 2130.86  4307.6 2119.76  4328.9 2114.41
  4359.2 2100.88  4381.2 2100.37  4429.6 2106.14  4460.5 2094.85  4481.8 2095.06
  4545.6 2082.16  4729.6 2074.25  4738.8 2071.23  4739.3 2070.73  4751.2 2071.23
    4781 2074.94  4994.7 2074.22  5012.8  2077.7  5066.8 2078.63  5127.5 2080.82
  5200.4 2090.18  5222.6 2093.78  5250.8  2103.5    5256 2102.23  5289.4  2117.6
  5294.6 2116.65  5322.8  2126.9  5367.2 2131.65  5404.5 2131.59  5408.4 2131.45
#Mann= 6 ,-1 , 0
  4234.5     .07       0  4545.6     .16       0  4738.8     .07       0
  4751.2     .16       0  5066.8     .07       0  5404.5    .035       0
Bank Sta=4738.8,4751.2
XS Rating Curve= 0 ,0
Exp/Cntr=0.3,0.1

Type RM Length L Ch R = 1 ,13298   ,192,192,192
BEGIN DESCRIPTION:
648
END DESCRIPTION:
XS GIS Cut Line= 3
      1532378.84       6781799.7      1531784.19      6781213.73
      1531636.61      6781027.08
#Sta/Elev= 30
  4162.7 2121.06  4173.7 2122.52  4180.8 2127.05  4194.9 2130.65  4209.1 2129.06
  4251.5 2117.19  4350.5 2105.89  4371.7 2101.29  4378.7 2096.86  4392.8 2093.13
  4484.8 2078.42    4515 2076.47  4563.9 2073.21  4612.1 2072.49  4620.1 2070.52
  4620.6 2070.02  4632.5 2070.52  4640.4 2072.72  4684.9 2072.63  4746.4 2072.24
  4760.6 2074.79  5015.8 2072.36  5065.5 2074.81  5144.1 2085.84  5164.9 2092.37
  5171.2  2096.6  5179.3 2097.18  5193.7 2102.57    5234 2120.27  5235.5 2120.27
#Mann= 7 ,-1 , 0
  4162.7     .07       0    4515     .16       0  4563.9     .07       0
  4620.1     .07       0  4632.5     .07       0  4684.9     .16       0
    5234     .07       0
Bank Sta=4620.1,4632.5
XS Rating Curve= 0 ,0
Exp/Cntr=0.3,0.1

Type RM Length L Ch R = 1 ,13106   ,156,156,156
BEGIN DESCRIPTION:
647
END DESCRIPTION:
XS GIS Cut Line= 3
      1532708.66      6781673.79      1531944.78      6781118.24
      1531771.17      6780914.25
#Sta/Elev= 30
  4040.9 2088.49  4262.5 2089.49  4312.8 2097.72  4413.2  2102.5  4441.1 2099.43
  4484.3 2080.26  4497.4  2077.1  4517.8 2073.42  4570.1 2070.01    4706 2070.98
  4812.8 2071.55  4821.3 2069.15  4821.8 2068.65  4833.7 2069.15  4849.1 2071.17
  4877.7 2069.64  4898.6 2072.74  4992.6 2070.66  5077.7 2072.53  5119.9 2077.88
  5148.5 2085.38  5156.2 2091.47  5191.5 2109.16  5197.9 2109.21  5205.6 2115.18
  5212.2 2115.05  5219.9 2121.36  5226.5 2121.43  5234.2 2126.61  5253.3 2129.53
#Mann= 7 ,-1 , 0
  4040.9     .07       0  4497.4     .16       0  4517.8     .07       0
    4706     .16       0  4821.3     .07       0  4833.7     .16       0
  5191.5     .07       0
Bank Sta=4821.3,4833.7
XS Rating Curve= 0 ,0
Exp/Cntr=0.3,0.1

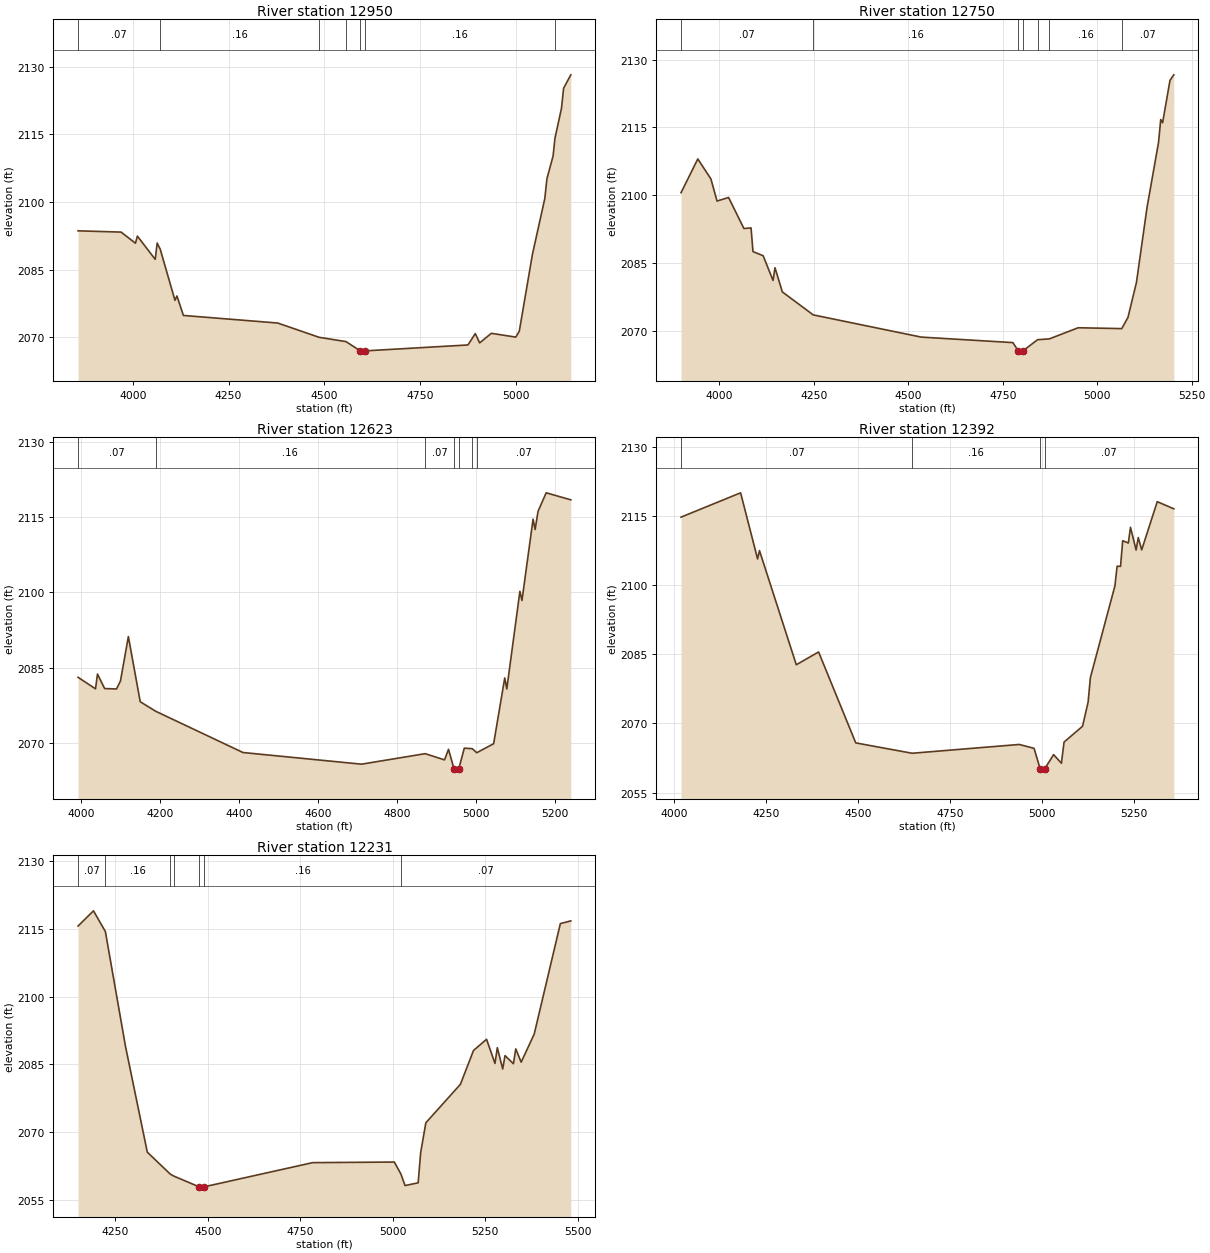
Type RM Length L Ch R = 1 ,12950   ,200,200,200
BEGIN DESCRIPTION:
646
END DESCRIPTION:
XS GIS Cut Line= 3
      1533125.34      6781192.02      1532009.89      6780975.01
      1531876.93       6780902.1
#Sta/Elev= 30
  3856.6  2093.6    3969 2093.32  4006.6 2090.86  4011.7 2092.43  4058.3 2087.28
  4063.4  2090.9  4071.4 2089.53  4109.9  2078.2    4115 2079.17    4132 2074.85
  4378.4 2073.17  4486.9    2070  4556.8 2069.06  4594.4    2067  4594.9  2066.5
  4606.8    2067  4875.7 2068.31  4894.9 2070.83  4906.3 2068.77  4936.8 2070.89
  5000.7 2070.05  5009.9 2071.36  5044.3 2088.41  5076.5 2100.72  5082.2 2105.16
  5098.3  2110.2  5103.1 2114.11  5120.1 2120.72  5125.8 2125.22  5144.6 2128.17
#Mann= 7 ,-1 , 0
  3856.6     .07       0  4071.4     .16       0  4486.9     .07       0
  4556.8     .16       0  4594.4     .07       0  4606.8     .16       0
  5103.1     .07       0
Bank Sta=4594.4,4606.8
XS Rating Curve= 0 ,0
Exp/Cntr=0.3,0.1

Type RM Length L Ch R = 1 ,12750   ,127,127,127
BEGIN DESCRIPTION:
13
END DESCRIPTION:
XS GIS Cut Line= 3
      1533188.71      6781007.13      1532105.43      6780808.18
      1531905.04      6780837.99
#Sta/Elev= 30
  3898.6 2100.52    3943    2108  3977.7 2103.56  3993.9 2098.67  4024.4 2099.47
    4065 2092.59  4083.9 2092.72    4089 2087.48  4115.9 2086.56  4142.1 2081.08
  4147.2  2083.9  4166.7 2078.55  4248.4 2073.46  4534.1 2068.54  4776.8 2067.32
  4790.9 2065.49  4791.4 2064.99  4803.3 2065.49  4842.3 2067.97  4873.1 2068.14
  4949.6 2070.61  5064.9 2070.42  5081.3  2072.9  5103.7 2080.63  5131.9 2097.34
  5162.2 2111.65    5168 2116.73    5173 2116.02  5192.5 2125.41  5202.6 2126.63
#Mann= 7 ,-1 , 0
  3898.6     .07       0  4248.4     .16       0  4790.9     .07       0
  4803.3     .16       0  4842.3     .07       0  4873.1     .16       0
  5064.9     .07       0
Bank Sta=4790.9,4803.3
XS Rating Curve= 0 ,0
Exp/Cntr=0.3,0.1

Type RM Length L Ch R = 1 ,12623   ,231,231,231
BEGIN DESCRIPTION:
645
END DESCRIPTION:
XS GIS Cut Line= 3
       1533112.3      6780714.59      1532109.71      6780679.87
      1531875.38      6780749.31
#Sta/Elev= 30
  3992.4 2083.04  4036.6 2080.74  4041.6 2083.69  4059.7 2080.79  4089.8 2080.71
  4099.8 2082.31  4119.8 2091.19  4149.8 2078.16  4188.7 2076.26    4410    2068
  4710.1 2065.67  4871.2 2067.77  4920.3 2066.53  4930.3 2068.64  4944.1 2064.78
  4944.6 2064.28  4956.5 2064.78  4970.3 2068.87  4990.5 2068.77  5001.8 2067.96
  5044.6 2069.76  5072.7 2082.91  5077.9 2080.72  5111.1 2100.24  5116.3  2098.4
  5144.4 2114.66  5149.6 2112.59    5157 2116.23  5177.6 2119.93    5240 2118.53
#Mann= 7 ,-1 , 0
  3992.4     .07       0  4188.7     .16       0  4871.2     .07       0
  4944.1     .07       0  4956.5     .07       0  4990.5     .16       0
  5001.8     .07       0
Bank Sta=4944.1,4956.5
XS Rating Curve= 0 ,0
Exp/Cntr=0.3,0.1

Type RM Length L Ch R = 1 ,12392   ,161,161,161
BEGIN DESCRIPTION:
644
END DESCRIPTION:
XS GIS Cut Line= 3
       1533125.3      6780323.97      1532166.14      6780458.52
      1531853.63      6780658.17
#Sta/Elev= 30
  4018.2 2114.81  4180.1 2120.09  4226.3 2105.73  4231.4 2107.55  4331.5 2082.75
  4392.1 2085.53  4493.1 2065.78  4646.3 2063.53  4937.4 2065.44  4977.8  2064.6
  4994.3 2060.15  4994.8 2059.65  5006.7 2060.15  5030.9 2063.23  5052.1 2061.37
  5059.3 2065.96  5109.6  2069.4  5124.8 2074.69  5130.8 2079.94  5197.6  2099.9
  5203.5 2104.15  5212.8 2104.12  5218.7 2109.69    5234 2109.19  5239.9  2112.6
  5255.1 2107.67    5261 2110.38  5270.3  2107.7  5312.6 2118.17  5357.6 2116.62
#Mann= 4 ,-1 , 0
  4018.2     .07       0  4646.3     .16       0  4994.3     .07       0
  5006.7     .07       0
Bank Sta=4994.3,5006.7
XS Rating Curve= 0 ,0
Exp/Cntr=0.3,0.1

Type RM Length L Ch R = 1 ,12231   ,377,377,377
BEGIN DESCRIPTION:
643
END DESCRIPTION:
XS GIS Cut Line= 3
      1532795.49      6779942.01      1532053.29      6780363.03
      1531671.86      6780653.44
#Sta/Elev= 30
  4149.2 2115.68  4190.9 2119.05  4223.1 2114.46  4277.4 2089.05  4336.5 2065.56
  4398.6  2060.7  4407.9 2060.27  4476.9 2057.87  4477.4 2057.37  4489.4 2057.87
  4783.7 2063.24  5004.6 2063.37  5022.4 2060.71  5033.6 2058.16    5069 2058.77
  5075.8 2065.46  5089.8 2072.07  5183.3  2080.6  5218.7  2088.1    5254 2090.58
  5276.8 2085.23  5283.1 2088.71  5297.7    2084  5303.9 2086.96  5326.7 2085.17
    5333 2088.45  5347.6 2085.51  5382.9 2091.73  5453.6 2116.22  5481.9 2116.82
#Mann= 7 ,-1 , 0
  4149.2     .07       0  4223.1     .16       0  4398.6     .07       0
  4407.9     .16       0  4476.9     .07       0  4489.4     .16       0
  5022.4     .07       0
Bank Sta=4476.9,4489.4
XS Rating Curve= 0 ,0
Exp/Cntr=0.3,0.1