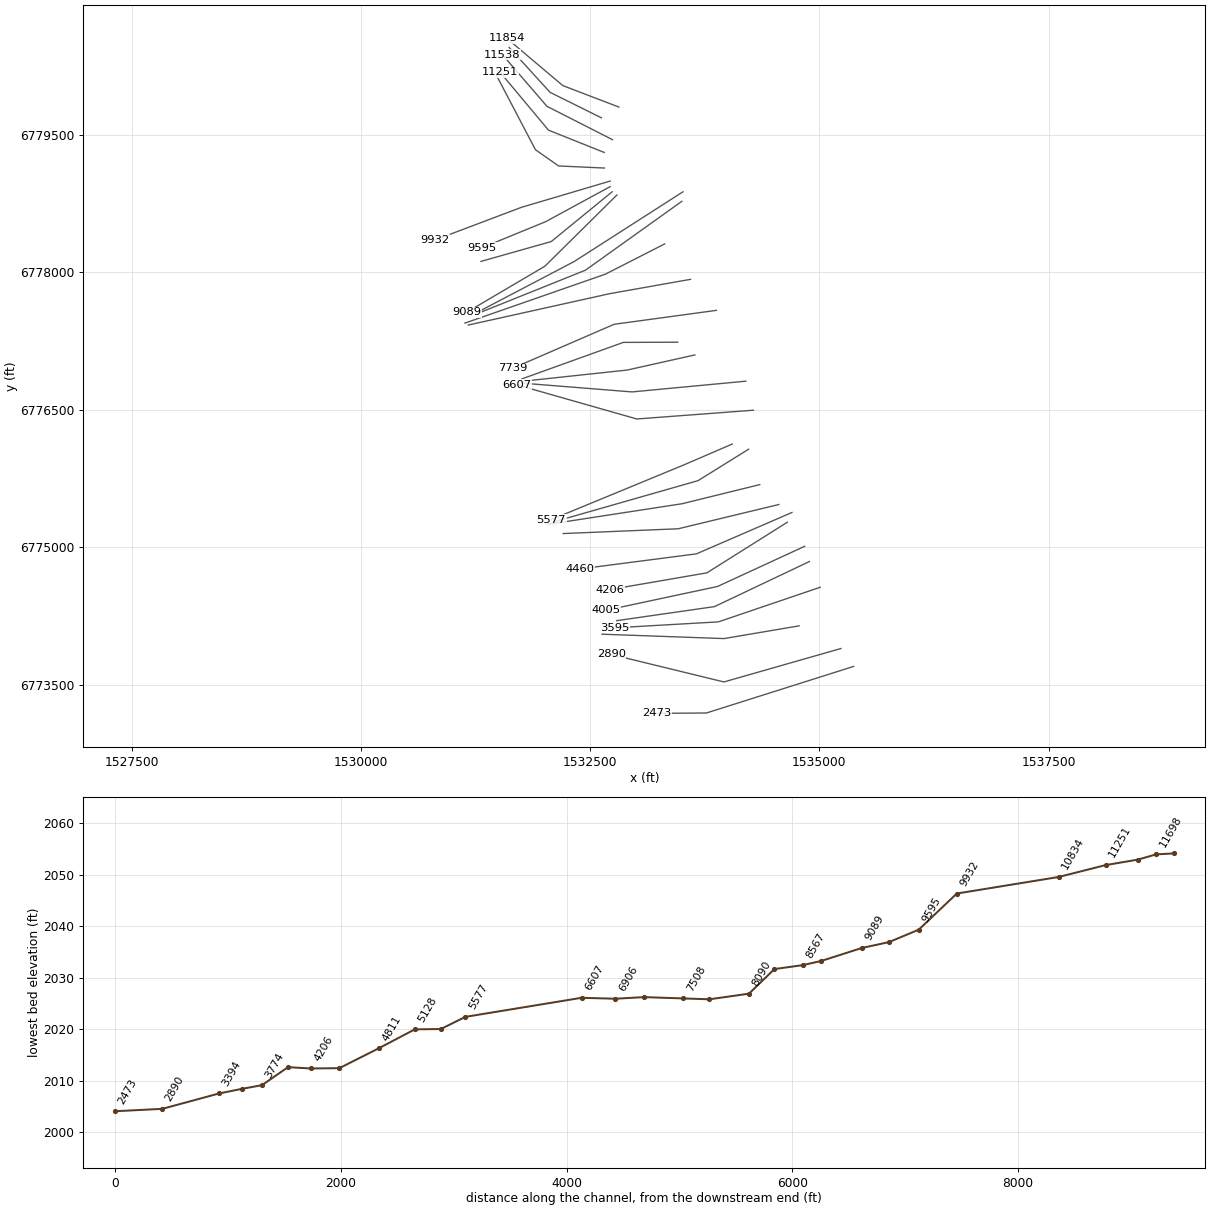
HEC-RAS study Elm 85.prj: Elm 85 Base Level Engineering

--- Elm 85.g01 (geometry) --- (continued)

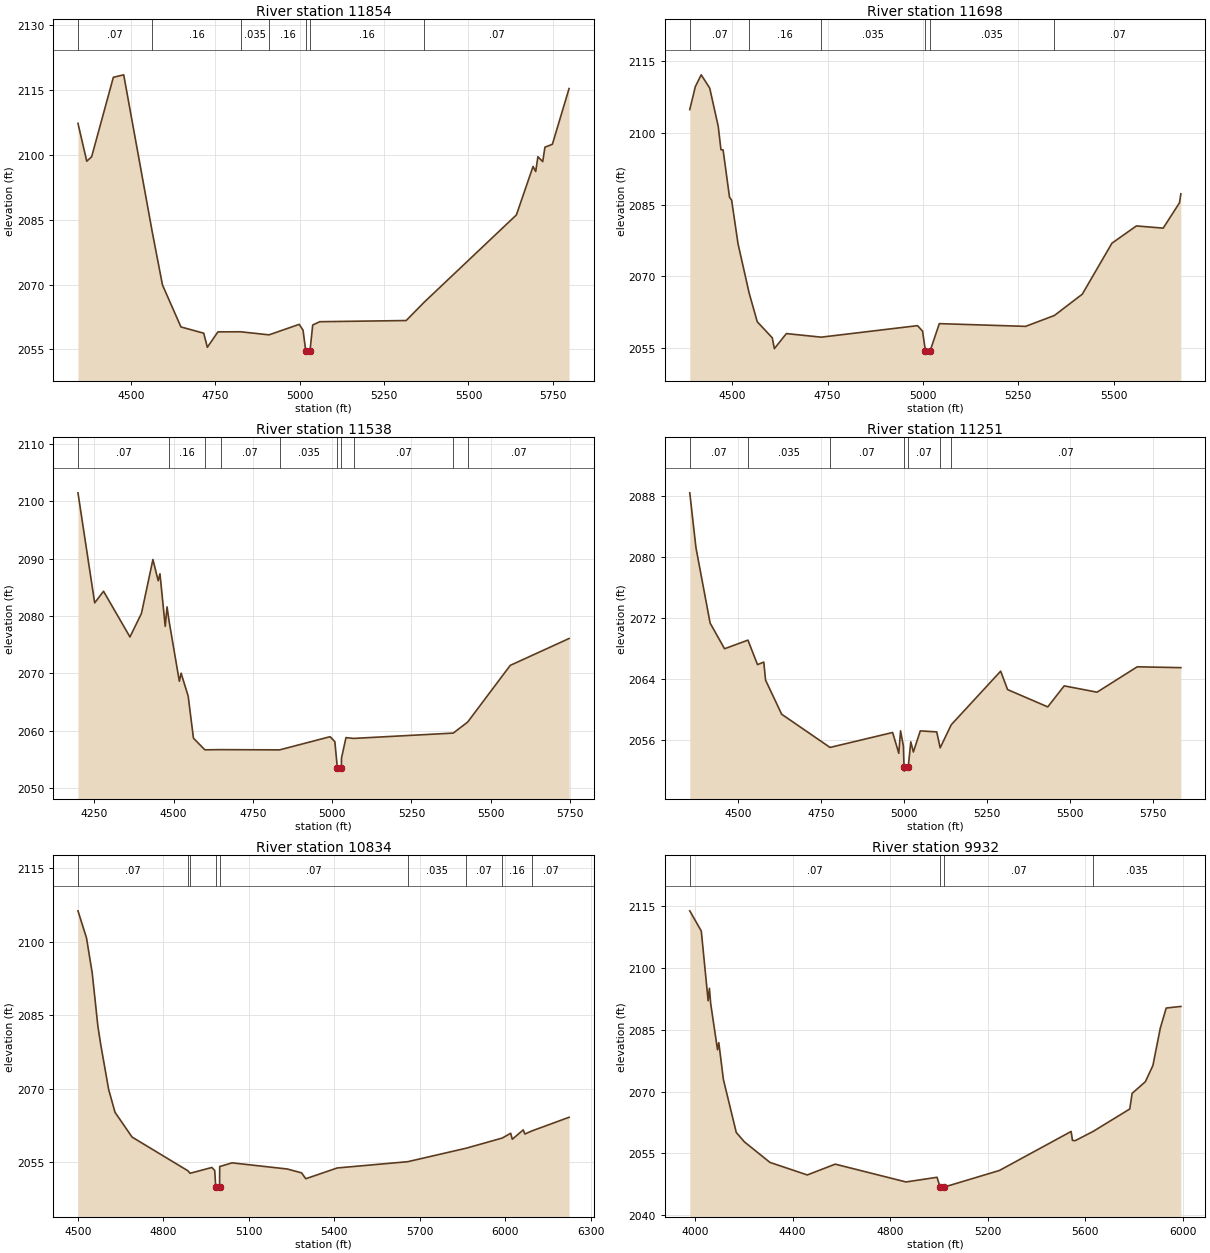
Type RM Length L Ch R = 1 ,11854   ,156,156,156
BEGIN DESCRIPTION:
639
END DESCRIPTION:
XS GIS Cut Line= 3
      1532812.84      6779803.14      1532200.86      6780037.51
      1531590.04      6780553.02
#Sta/Elev= 30
  4343.3 2107.29  4369.3 2098.53  4383.8 2099.56  4448.1 2117.95  4478.8 2118.52
  4563.3 2082.18  4593.6  2069.9  4648.3 2060.18  4715.8 2058.73  4726.5 2055.47
  4757.8 2059.04  4825.2 2059.06  4909.2 2058.35  4998.6 2060.78    5010 2059.42
    5018 2054.62  5018.5 2054.12  5030.5 2054.62  5038.6 2060.63  5059.4 2061.39
  5315.5 2061.66  5367.8 2065.83  5641.9  2086.1  5691.3 2097.33  5699.1 2096.14
  5705.6 2099.57  5719.9 2098.44  5726.4 2101.78  5748.5 2102.45  5797.9 2115.34
#Mann= 7 ,-1 , 0
  4343.3     .07       0  4563.3     .16       0  4825.2    .035       0
  4909.2     .16       0    5018     .07       0  5030.5     .16       0
  5367.8     .07       0
Bank Sta=5018,5030.5
XS Rating Curve= 0 ,0
Exp/Cntr=0.3,0.1

Type RM Length L Ch R = 1 ,11698   ,160,160,160
BEGIN DESCRIPTION:
640
END DESCRIPTION:
XS GIS Cut Line= 3
      1532621.86      6779685.95      1532061.97      6779963.73
      1531615.48      6780453.56
#Sta/Elev= 30
  4388.8 2104.88  4403.4 2109.69  4418.8 2112.15  4441.1 2109.38  4463.4  2101.4
  4470.6 2096.49  4476.2 2096.44    4493 2086.57  4498.6 2085.91  4515.4  2076.8
  4544.6 2066.47  4565.8 2060.49  4605.1 2057.14  4610.7 2054.87  4642.1 2058.02
  4733.6 2057.27  4986.1 2059.68  4999.3 2058.53  5006.7 2054.43  5007.2 2053.93
  5019.2 2054.43  5043.2  2060.1  5269.5 2059.53  5345.1 2061.81  5418.1 2066.26
  5495.9 2076.93    5560 2080.54  5630.3 2080.08  5672.9 2085.36  5676.6 2087.26
#Mann= 6 ,-1 , 0
  4388.8     .07       0  4544.6     .16       0  4733.6    .035       0
  5006.7    .035       0  5019.2    .035       0  5345.1     .07       0
Bank Sta=5006.7,5019.2
XS Rating Curve= 0 ,0
Exp/Cntr=0.3,0.1

Type RM Length L Ch R = 1 ,11538   ,287,287,287
BEGIN DESCRIPTION:
642
END DESCRIPTION:
XS GIS Cut Line= 3
      1532743.37      6779447.24      1532027.25      6779811.82
      1531541.16      6780376.02
#Sta/Elev= 30
  4198.7  2101.5  4251.4 2082.29  4279.3 2084.32  4362.6 2076.34  4398.9 2080.46
    4435 2089.86  4451.6 2086.16  4457.2 2087.37  4473.8  2078.2  4479.5 2081.59
  4486.1 2079.06  4518.3 2068.61  4523.9 2070.01  4546.2    2066  4562.8 2058.67
  4598.8 2056.64  4649.2 2056.67  4834.4 2056.63  4993.6 2058.93  5008.6 2058.06
  5016.6 2053.42  5017.1 2052.92  5029.1 2053.42  5029.5 2055.19  5043.7 2058.77
  5067.9 2058.63  5381.9 2059.56  5427.4 2061.49  5561.6 2071.38    5747 2076.07
#Mann= 10 ,-1 , 0
  4198.7     .07       0  4486.1     .16       0  4598.8    .035       0
  4649.2     .07       0  4834.4    .035       0  5016.6    .035       0
  5029.1    .035       0  5067.9     .07       0  5381.9     .16       0
  5427.4     .07       0
Bank Sta=5016.6,5029.1
XS Rating Curve= 0 ,0
Exp/Cntr=0.3,0.1

Type RM Length L Ch R = 1 ,11251   ,417,417,417
BEGIN DESCRIPTION:
641
END DESCRIPTION:
XS GIS Cut Line= 3
      1532652.25      6779308.34      1532044.61       6779551.4
      1531515.95      6780184.05
#Sta/Elev= 30
  4355.5 2088.37  4374.1 2081.19  4416.8 2071.28  4460.2 2067.91  4530.7 2069.04
  4559.5 2065.83  4578.4 2066.16  4583.8 2063.79  4632.2 2059.32  4777.9 2054.96
  4966.4 2056.92    4985 2054.19  4990.3 2057.13  4998.8 2055.14  5000.8 2052.35
  5001.3 2051.85  5013.3 2052.35  5021.1 2055.69  5028.9 2054.36  5049.7 2057.13
  5099.2    2057  5109.6 2054.91  5142.8 2057.93  5291.8 2064.97  5312.6 2062.55
  5433.6 2060.28  5483.1 2063.04    5582 2062.21    5703 2065.54  5834.4 2065.43
#Mann= 7 ,-1 , 0
  4355.5     .07       0  4530.7    .035       0  4777.9     .07       0
  5000.8     .07       0  5013.3     .07       0  5109.6    .035       0
  5142.8     .07       0
Bank Sta=5000.8,5013.3
XS Rating Curve= 0 ,0
Exp/Cntr=0.3,0.1

Type RM Length L Ch R = 1 ,10834   ,902,902,902
BEGIN DESCRIPTION:
12
END DESCRIPTION:
XS GIS Cut Line= 4
      1532654.95        6779138.      1532155.07      6779160.69
      1531902.63      6779337.53      1531477.26       6780149.2
#Sta/Elev= 30
  4499.6 2106.33  4529.6  2100.8  4549.6 2093.66  4569.6 2082.78  4579.6 2079.03
  4607.3  2069.9  4629.7 2065.22  4689.7 2060.16  4886.2 2053.27  4893.1 2052.77
    4970 2053.96    4980 2053.33  4983.4 2050.04  4983.9 2049.54  4996.8 2050.04
  4997.5 2054.15  5040.9  2054.9  5234.4 2053.65    5285 2052.86  5299.8 2051.66
  5410.4 2053.86  5658.1 2055.14  5863.8  2057.9  5989.7 2059.96  6019.6 2060.94
  6025.2 2059.72  6063.7 2061.63  6069.4 2060.78  6094.2 2061.42  6224.6  2064.2
#Mann= 9 ,-1 , 0
  4499.6     .07       0  4886.2    .035       0  4893.1     .07       0
  4983.4     .07       0  4996.8     .07       0  5658.1    .035       0
  5863.8     .07       0  5989.7     .16       0  6094.2     .07       0
Bank Sta=4983.4,4996.8
XS Rating Curve= 0 ,0
Exp/Cntr=0.3,0.1

Type RM Length L Ch R = 1 ,9932    ,337,337,337
BEGIN DESCRIPTION:
638
END DESCRIPTION:
XS GIS Cut Line= 3
      1532717.37      6778995.85      1531749.47      6778709.39
      1530808.79      6778353.92
#Sta/Elev= 30
  3978.1 2113.84  4025.4 2108.94  4053.5 2092.03  4058.7 2095.05    4064  2091.3
    4092 2080.14  4097.2 2081.86  4116.1 2072.92  4168.9 2060.08  4202.2  2057.8
  4307.2 2052.81  4460.3 2049.77    4575 2052.39  4865.4 2048.07  4992.6  2049.2
  5005.4 2046.83  5005.9 2046.33  5021.9 2046.83  5248.8 2050.86  5542.9 2060.32
  5548.3 2058.17  5558.9 2058.07  5632.9 2060.32  5783.4 2065.77  5793.2 2069.56
  5847.5 2072.39  5878.4 2076.32  5908.6 2085.36    5933 2090.26  5993.1 2090.65
#Mann= 4 ,-1 , 0
  3978.1     .07       0  5005.4     .07       0  5021.9     .07       0
  5632.9    .035       0
Bank Sta=5005.4,5021.9
XS Rating Curve= 0 ,0
Exp/Cntr=0.3,0.1

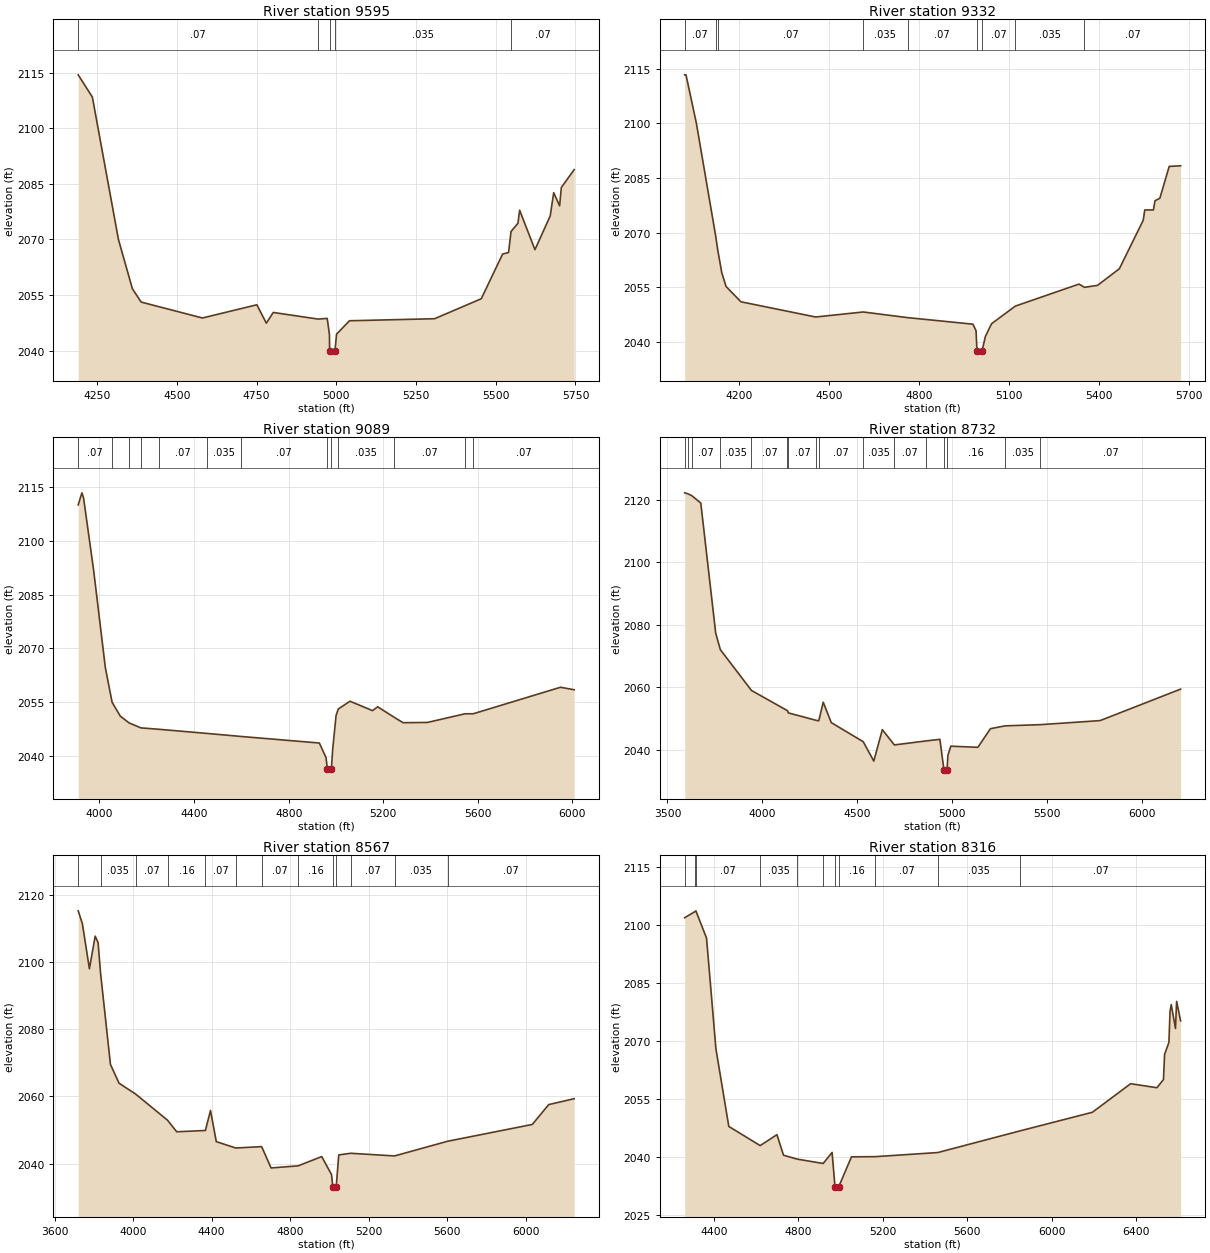
Type RM Length L Ch R = 1 ,9595    ,263,263,263
BEGIN DESCRIPTION:
637
END DESCRIPTION:
XS GIS Cut Line= 3
      1532717.39       6778935.1      1532014.23      6778553.14
      1531315.47      6778266.69
#Sta/Elev= 30
  4190.4  2114.4  4234.8 2108.39  4316.6 2069.97  4360.3  2056.7  4387.8 2053.09
    4580  2048.8  4750.7 2052.36  4780.3 2047.41  4802.2 2050.29  4943.3  2048.5
  4971.3 2048.69  4978.3 2044.38    4979 2039.82  4979.5 2039.32  4995.6 2039.82
  5000.6 2044.43  5041.1 2048.05    5308  2048.6  5454.5 2053.99  5521.5 2066.05
  5540.1 2066.47  5547.8 2072.12  5569.5 2074.36  5574.9 2077.86  5622.9 2067.23
  5670.7 2076.33  5681.7 2082.61  5700.2 2079.07  5705.6 2084.01  5745.8 2088.82
#Mann= 5 ,-1 , 0
  4190.4     .07       0  4943.3    .035       0    4979    .035       0
  4995.6    .035       0  5547.8     .07       0
Bank Sta=4979,4995.6
XS Rating Curve= 0 ,0
Exp/Cntr=0.3,0.1

Type RM Length L Ch R = 1 ,9332    ,243,243,243
BEGIN DESCRIPTION:
636
END DESCRIPTION:
XS GIS Cut Line= 3
      1532739.02      6778878.63      1532074.99      6778336.12
      1531308.36      6778119.56
#Sta/Elev= 30
  4017.7 2113.33  4022.1 2113.33  4056.7 2100.04  4120.8 2069.22  4127.9 2065.28
  4141.4 2059.01  4155.8  2055.2  4205.3 2051.01  4454.4 2046.83  4613.2 2048.21
    4761 2046.66  4979.1 2044.86  4989.5 2043.07  4992.7 2037.41  4993.2 2036.91
  5009.3 2037.41  5020.6 2041.49  5041.4    2045  5120.5 2049.82  5332.8 2055.87
  5351.1 2054.98  5394.7 2055.52  5467.5 2060.08  5547.1  2073.4  5552.3 2076.23
  5581.1 2076.22  5586.3 2078.73  5602.6 2079.45  5633.7 2088.18  5671.8 2088.35
#Mann= 9 ,-1 , 0
  4017.7     .07       0  4120.8    .035       0  4127.9     .07       0
  4613.2    .035       0    4761     .07       0  4992.7     .07       0
  5009.3     .07       0  5120.5    .035       0  5351.1     .07       0
Bank Sta=4992.7,5009.3
XS Rating Curve= 0 ,0
Exp/Cntr=0.3,0.1

Type RM Length L Ch R = 1 ,9089    ,357,357,357
BEGIN DESCRIPTION:
635
END DESCRIPTION:
XS GIS Cut Line= 3
       1532791.1       6778843.9      1532005.55      6778067.02
      1531150.49      6777563.54
#Sta/Elev= 30
    3910 2110.01  3925.6 2113.37  3932.6 2111.98    3975 2091.88  4024.6 2064.68
  4053.3 2054.95  4088.2 2051.07  4125.5 2049.18  4175.3 2047.81    4253 2047.41
  4455.7 2046.26  4598.2 2045.42  4929.7 2043.59    4958 2039.51  4963.8 2036.25
  4964.3 2035.75  4980.4 2036.25  4986.3    2042  5000.4 2051.28  5009.9 2053.08
  5059.1 2055.25  5154.7 2052.62  5176.3 2053.69  5244.1 2050.85  5283.6 2049.26
  5386.8 2049.33  5546.2 2051.75    5580 2051.74  5949.3 2059.14  6007.1 2058.45
#Mann= 13 ,-1 , 0
    3910     .07       0  4053.3    .035       0  4125.5     .07       0
  4175.3    .035       0    4253     .07       0  4455.7    .035       0
  4598.2     .07       0  4963.8     .07       0  4980.4     .07       0
  5009.9    .035       0  5244.1     .07       0  5546.2    .035       0
    5580     .07       0
Bank Sta=4963.8,4980.4
XS Rating Curve= 0 ,0
Exp/Cntr=0.3,0.1

Type RM Length L Ch R = 1 ,8732    ,165,165,165
BEGIN DESCRIPTION:
634
END DESCRIPTION:
XS GIS Cut Line= 3
      1533511.65      6778878.67      1532326.73      6778119.11
      1531259.53      6777559.48
#Sta/Elev= 30
  3590.6 2122.19    3607 2121.89  3627.1 2121.32  3675.5 2118.93  3754.1 2077.33
  3778.7 2072.05  3942.5 2059.03    4132 2052.57  4137.1 2051.85  4284.1 2049.47
    4297 2049.34  4320.5 2055.28  4362.7 2048.76  4531.1 2042.66  4586.8 2036.46
  4631.9  2046.5  4695.1 2041.62  4863.2 2042.91    4935 2043.41  4956.2 2033.75
  4956.7 2033.25  4972.8 2033.75  4977.3 2038.29  4992.5 2041.22  5135.1 2040.86
  5201.3 2046.81  5278.1 2047.72  5464.8  2048.1  5779.1  2049.4  6203.1 2059.46
#Mann= 16 ,-1 , 0
  3590.6     .07       0    3607    .035       0  3627.1     .07       0
  3778.7    .035       0  3942.5     .07       0    4132     .16       0
  4137.1     .07       0  4284.1     .16       0    4297     .07       0
  4531.1    .035       0  4695.1     .07       0  4863.2     .16       0
  4956.2     .07       0  4972.8     .16       0  5278.1    .035       0
  5464.8     .07       0
Bank Sta=4956.2,4972.8
XS Rating Curve= 0 ,0
Exp/Cntr=0.3,0.1

Type RM Length L Ch R = 1 ,8567    ,251,251,251
BEGIN DESCRIPTION:
633
END DESCRIPTION:
XS GIS Cut Line= 3
      1533498.61       6778774.5      1532448.25      6778023.62
      1531302.41      6777563.55
#Sta/Elev= 30
  3720.3 2115.18  3741.6 2111.35  3777.3 2097.96  3806.7 2107.66  3821.5 2105.75
    3834 2096.75  3884.5 2069.51  3928.4 2063.92  4012.7  2060.7  4175.3 2052.92
  4222.1 2049.48  4368.2 2049.87  4394.1 2055.82  4423.6 2046.55  4522.6 2044.66
  4654.7 2045.07  4702.5 2038.73  4840.3 2039.35  4960.5 2042.11  5010.4 2036.77
  5017.4 2032.93  5017.9 2032.43    5034 2032.93  5047.3  2042.6  5107.6 2043.09
  5331.6  2042.3  5601.4 2046.66  6033.1 2051.66  6116.5 2057.56  6246.2 2059.32
#Mann= 13 ,-1 , 0
  3720.3     .07       0    3834    .035       0  4012.7     .07       0
  4175.3     .16       0  4368.2     .07       0  4522.6    .035       0
  4654.7     .07       0  4840.3     .16       0  5017.4     .07       0
    5034     .16       0  5107.6     .07       0  5331.6    .035       0
  5601.4     .07       0
Bank Sta=5017.4,5034
XS Rating Curve= 0 ,0
Exp/Cntr=0.3,0.1

Type RM Length L Ch R = 1 ,8316    ,226,226,226
BEGIN DESCRIPTION:
632
END DESCRIPTION:
XS GIS Cut Line= 3
      1533311.99      6778310.09      1532665.27      6777980.22
      1531133.11      6777446.35
#Sta/Elev= 30
  4261.2  2101.8  4309.1 2103.35  4314.2 2103.58  4364.7 2096.55  4409.1 2067.96
  4470.2 2047.86  4618.8 2042.92  4698.1 2045.74  4729.3 2040.43  4793.6 2039.43
    4917  2038.3  4959.3 2041.15  4973.2 2032.17  4973.7 2031.67  4989.8 2032.17
    5051 2040.01  5163.1 2040.06  5459.6 2041.12    5850 2046.73  6191.9 2051.53
  6373.1 2058.91  6497.4 2057.87  6528.5 2059.99  6533.8  2066.5  6554.3 2069.59
  6559.6 2077.64  6565.3 2079.35  6585.4 2073.17  6590.7 2080.19  6609.7 2075.16
#Mann= 11 ,-1 , 0
  4261.2     .07       0  4309.1     .16       0  4314.2     .07       0
  4618.8    .035       0  4793.6     .07       0    4917     .16       0
  4973.2     .07       0  4989.8     .16       0  5163.1     .07       0
  5459.6    .035       0    5850     .07       0
Bank Sta=4973.2,4989.8
XS Rating Curve= 0 ,0
Exp/Cntr=0.3,0.1

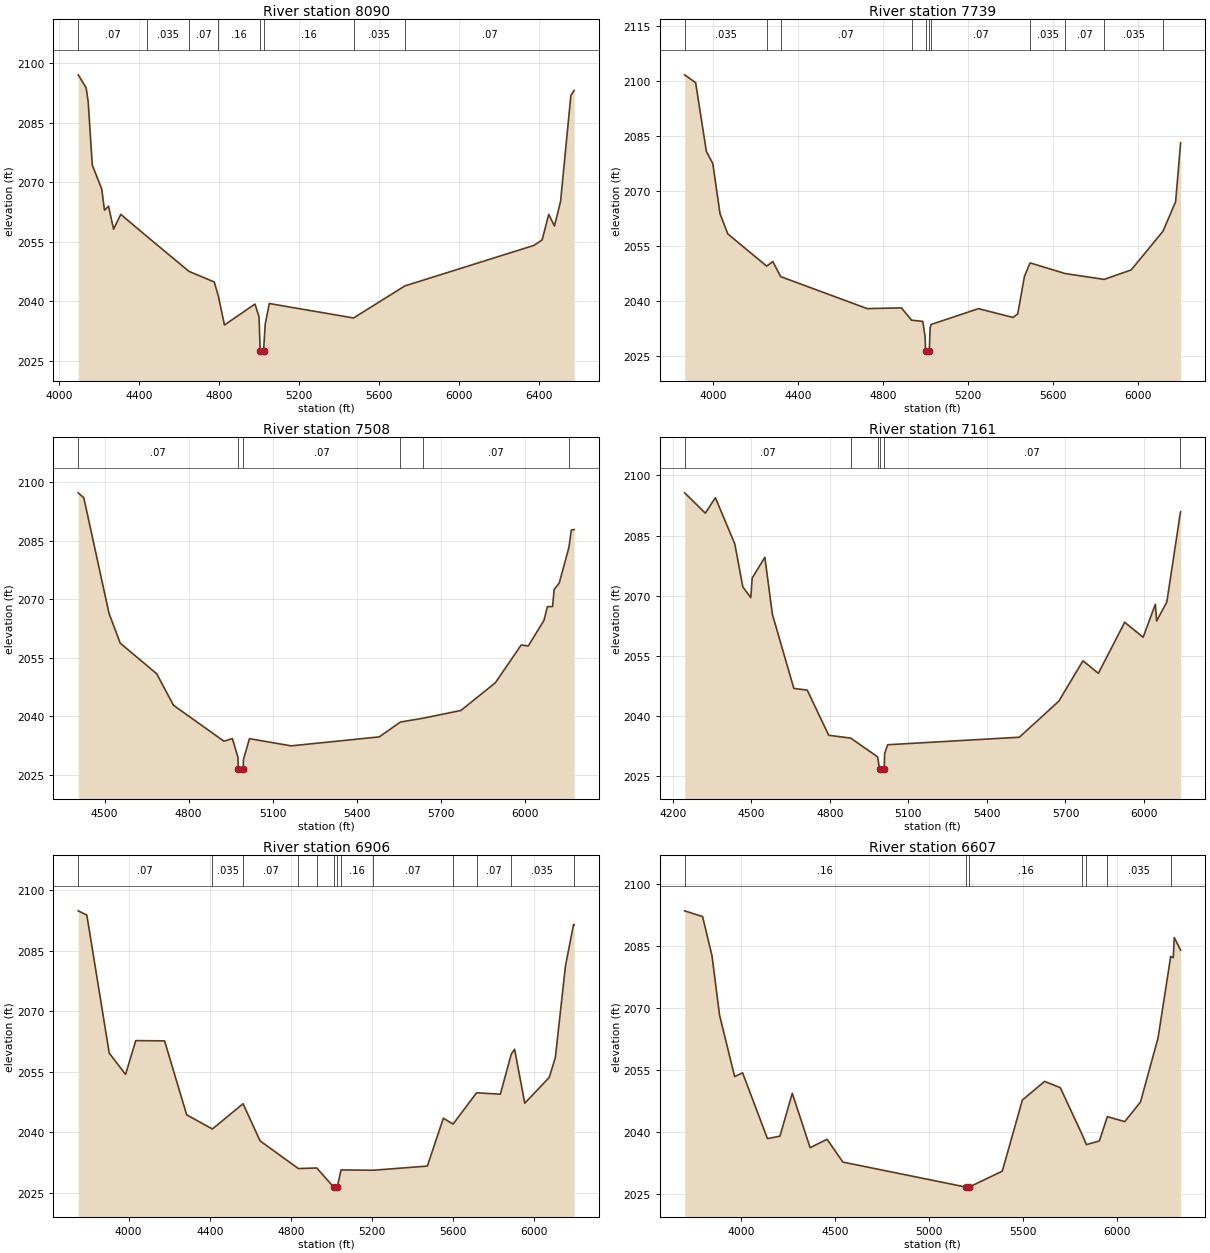
Type RM Length L Ch R = 1 ,8090    ,351,351,351
BEGIN DESCRIPTION:
631
END DESCRIPTION:
XS GIS Cut Line= 3
      1533594.09       6777923.8      1532713.01      6777767.55
       1531168.9      6777424.89
#Sta/Elev= 30
  4096.8 2097.13  4136.5 2093.86  4146.7  2090.3    4167 2074.37  4214.3  2068.3
  4227.9 2062.95  4248.2 2063.97  4273.4 2058.17  4309.2 2061.91  4441.3 2056.29
  4649.8 2047.53  4776.3 2044.84  4796.5  2041.3  4827.1 2033.99  4979.4 2039.27
  4999.8 2036.07  5005.5 2027.39    5006 2026.89  5022.3 2027.39  5030.6 2034.23
    5051 2039.41  5471.8 2035.76  5727.8 2043.85  6372.4 2054.08  6413.4 2055.46
  6446.4 2061.91  6474.9 2058.98  6505.6 2065.21  6556.8 2091.89  6573.3 2093.18
#Mann= 8 ,-1 , 0
  4096.8     .07       0  4441.3    .035       0  4649.8     .07       0
  4796.5     .16       0  5005.5     .07       0  5022.3     .16       0
  5471.8    .035       0  5727.8     .07       0
Bank Sta=5005.5,5022.3
XS Rating Curve= 0 ,0
Exp/Cntr=0.3,0.1

Type RM Length L Ch R = 1 ,7739    ,231,231,231
BEGIN DESCRIPTION:
630
END DESCRIPTION:
XS GIS Cut Line= 3
      1533876.17      6777585.25      1532760.75      6777433.34
      1531651.45      6776952.36
#Sta/Elev= 30
  3867.5 2101.73  3919.1  2099.6  3969.6 2080.84  3999.9 2077.53  4033.8 2063.87
  4070.5 2058.33  4253.8 2049.53  4282.5 2050.79  4319.1 2046.68  4726.5 2037.95
    4888 2038.14  4935.6 2034.79  4988.5 2034.46  4999.5  2030.2  5001.6  2026.3
  5002.1  2025.8  5019.1  2026.3    5023 2032.61  5026.9  2033.6  5250.5 2037.93
  5413.7 2035.53  5435.5 2036.53  5467.2 2046.75  5493.5 2050.42  5658.9 2047.51
  5842.3 2045.92  5969.3 2048.49  6119.3 2059.05  6178.8 2067.11  6202.3 2083.18
#Mann= 11 ,-1 , 0
  3867.5    .035       0  4253.8     .16       0  4319.1     .07       0
  4935.6     .16       0  5001.6     .07       0  5019.1     .16       0
  5026.9     .07       0  5493.5    .035       0  5658.9     .07       0
  5842.3    .035       0  6119.3     .07       0
Bank Sta=5001.6,5019.1
XS Rating Curve= 0 ,0
Exp/Cntr=0.3,0.1

Type RM Length L Ch R = 1 ,7508    ,347,347,347
BEGIN DESCRIPTION:
11
END DESCRIPTION:
XS GIS Cut Line= 3
        1533455.        6777238.       1532861.1      6777235.81
      1531754.97      6776837.99
#Sta/Elev= 30
  4406.1 2097.31  4426.1 2096.03  4516.1 2066.39  4556.1 2058.77  4686.1 2050.93
  4746.1 2042.85  4926.1 2033.64  4956.1 2034.31  4976.1 2029.48  4977.3 2026.47
  4977.8 2025.97  4994.9 2026.47  4995.6 2028.95  5017.1 2034.29  5165.9 2032.45
  5480.2 2034.75  5555.8 2038.56  5635.7 2039.52  5771.4 2041.52  5894.3 2048.62
  5986.4  2058.3  6011.8 2058.06    6068 2064.63  6079.8 2068.11  6098.7 2068.18
    6104 2072.52  6122.3  2074.2  6156.9 2083.32  6165.4 2087.78  6175.5 2087.89
#Mann= 6 ,-1 , 0
  4406.1     .07       0  4977.3     .07       0  4994.9     .07       0
  5555.8    .035       0  5635.7     .07       0  6156.9    .035       0
Bank Sta=4977.3,4994.9
XS Rating Curve= 0 ,0
Exp/Cntr=0.3,0.1

Type RM Length L Ch R = 1 ,7161    ,255,255,255
BEGIN DESCRIPTION:
629
END DESCRIPTION:
XS GIS Cut Line= 3
      1533641.79      6777099.13      1532903.98      6776934.21
      1531772.69      6776812.85
#Sta/Elev= 30
  4245.8 2095.65  4324.7 2090.58    4363 2094.44  4437.2 2082.91  4467.9 2072.17
  4498.3  2069.5  4503.5 2074.39    4552 2079.58  4580.7 2065.35  4662.6 2046.86
  4713.9 2046.43  4795.8 2035.16  4879.8 2034.46  4982.6 2029.78  4989.9 2026.72
  4990.4 2026.22  5007.5 2026.72  5009.5 2030.63  5020.9  2032.8  5523.8 2034.68
  5674.6 2043.68  5766.7 2053.75  5825.5 2050.62  5926.1 2063.36  5996.5 2059.61
  6043.1 2067.86  6048.1 2063.68    6087 2068.44  6138.9 2090.81  6139.6 2090.92
#Mann= 6 ,-1 , 0
  4245.8     .07       0  4879.8     .16       0  4982.6     .07       0
  4989.9     .07       0  5007.5     .07       0  6138.9    .035       0
Bank Sta=4989.9,5007.5
XS Rating Curve= 0 ,0
Exp/Cntr=0.3,0.1

Type RM Length L Ch R = 1 ,6906    ,299,299,299
BEGIN DESCRIPTION:
628
END DESCRIPTION:
XS GIS Cut Line= 3
      1534197.34      6776812.68      1532956.07       6776695.5
      1531762.48      6776790.98
#Sta/Elev= 30
  3751.8 2094.89  3794.3 2093.84  3904.8 2059.62  3985.2 2054.35  4035.4 2062.72
  4177.5 2062.66  4286.5 2044.31  4413.1 2040.82  4564.3 2047.08  4648.1 2037.87
  4836.9 2031.01  4927.7 2031.15  5010.9 2026.41  5011.4 2025.91  5028.5 2026.41
  5047.2 2030.67  5205.2 2030.59  5472.5 2031.62  5551.4 2043.49  5599.4 2042.04
  5715.1 2049.79  5832.3 2049.44  5885.9 2059.36  5902.5 2060.58  5952.7 2047.21
  6073.1 2053.59  6103.2  2058.5  6153.3 2081.26  6192.9 2091.48    6196 2091.48
#Mann= 13 ,-1 , 0
  3751.8     .07       0  4413.1    .035       0  4564.3     .07       0
  4836.9     .16       0  4927.7     .07       0  5010.9     .07       0
  5028.5     .07       0  5047.2     .16       0  5205.2     .07       0
  5599.4    .035       0  5715.1     .07       0  5885.9    .035       0
  6192.9     .07       0
Bank Sta=5010.9,5028.5
XS Rating Curve= 0 ,0
Exp/Cntr=0.3,0.1

Type RM Length L Ch R = 1 ,6607    ,1030,1030,1030
BEGIN DESCRIPTION:
627
END DESCRIPTION:
XS GIS Cut Line= 3
      1534279.82      6776495.84      1533008.15      6776400.36
      1531699.81      6776772.93
#Sta/Elev= 30
  3701.9 2093.49    3797  2092.1  3847.1 2082.61  3887.2 2068.24  3967.5 2053.34
  4009.8 2054.26  4141.7 2038.33  4208.1 2038.91  4273.7  2049.3  4368.6 2036.13
  4458.8 2038.16  4542.6 2032.64  5196.1 2026.59  5196.6 2026.09  5213.7 2026.59
  5389.8 2030.44  5496.5 2047.67  5614.7 2052.18  5697.9 2050.67  5814.3 2039.29
  5836.8 2036.87  5905.8 2037.76    5948 2043.64  6040.7 2042.44  6124.2 2047.18
  6217.7 2062.73  6284.8 2082.44  6298.5 2082.15  6303.7 2087.04  6337.5 2083.99
#Mann= 7 ,-1 , 0
  3701.9     .16       0  5196.1     .07       0  5213.7     .16       0
  5814.3    .035       0  5836.8     .07       0    5948    .035       0
  6284.8     .07       0
Bank Sta=5196.1,5213.7
XS Rating Curve= 0 ,0
Exp/Cntr=0.3,0.1

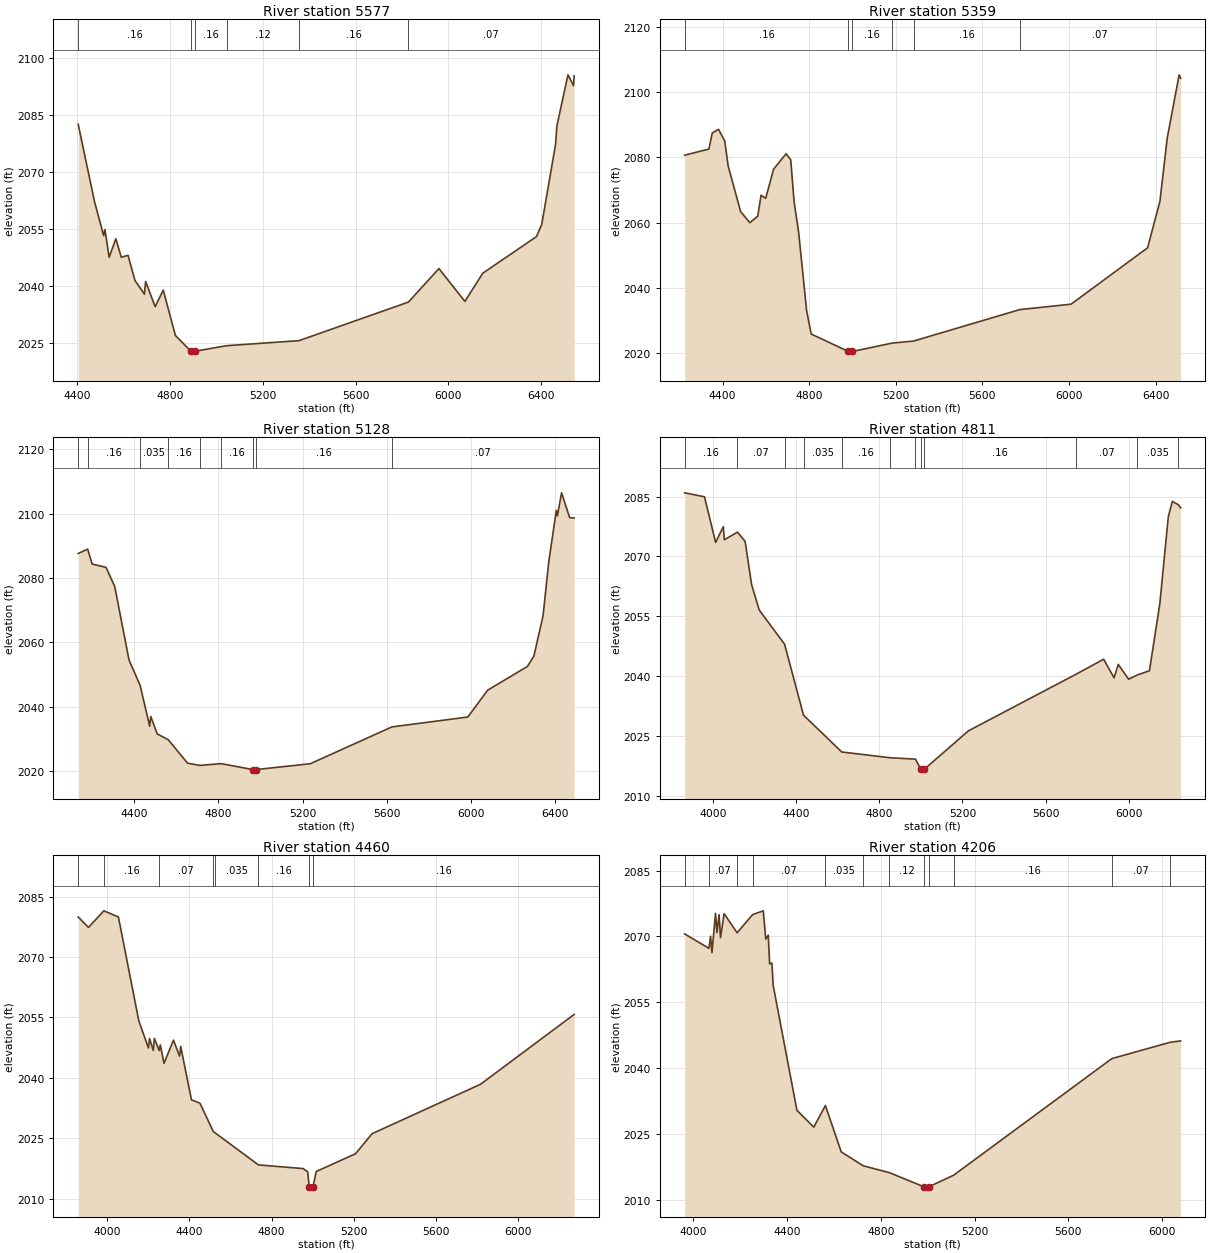
Type RM Length L Ch R = 1 ,5577    ,218,218,218
BEGIN DESCRIPTION:
625
END DESCRIPTION:
XS GIS Cut Line= 3
       1534049.8      6776126.92      1533515.96      6775896.89
      1532075.85      6775302.62
#Sta/Elev= 30
  4403.4 2082.64    4474  2062.2  4513.2 2053.32  4518.7 2054.92  4536.8 2047.62
  4565.7 2052.51  4589.2 2047.62  4618.2 2048.15  4648.2 2041.52  4688.8 2037.92
  4694.2 2041.25  4735.3 2034.63  4770.2 2038.99  4822.7 2027.03  4889.8 2022.89
  4890.3 2022.39  4907.8 2022.89  5043.5 2024.35  5355.5 2025.67  5827.8 2035.83
  5959.3 2044.66  6071.3 2036.01  6148.5 2043.43  6380.1 2053.07  6402.9  2056.3
  6462.7 2077.45  6468.1 2082.18  6515.9 2095.67  6539.9 2092.81  6542.6 2095.41
#Mann= 6 ,-1 , 0
  4403.4     .16       0  4889.8     .07       0  4907.8     .16       0
  5043.5     .12       0  5355.5     .16       0  5827.8     .07       0
Bank Sta=4889.8,4907.8
XS Rating Curve= 0 ,0
Exp/Cntr=0.3,0.1

Type RM Length L Ch R = 1 ,5359    ,231,231,231
BEGIN DESCRIPTION:
626
END DESCRIPTION:
XS GIS Cut Line= 3
      1534227.78       6776070.5      1533676.55      6775727.62
      1532098.37      6775276.71
#Sta/Elev= 30
  4224.9 2080.63  4336.9 2082.51  4352.3 2087.41  4381.3 2088.55  4410.1 2084.95
  4425.5  2077.4  4483.3 2063.35  4525.8 2059.97  4562.4 2061.94  4577.7 2068.37
    4599  2067.4  4635.6 2076.36  4693.4 2081.07  4714.7 2079.22    4730 2066.53
  4751.3 2056.95  4787.9 2033.15  4809.1 2025.88  4981.1 2020.53  4981.6 2020.03
  4999.1 2020.53  5182.1 2023.09  5281.8 2023.72    5773 2033.36  6009.3 2035.01
  6362.9 2052.27  6419.9 2066.53  6453.7  2085.9  6508.5 2105.23  6515.4 2104.19
#Mann= 6 ,-1 , 0
  4224.9     .16       0  4981.1     .07       0  4999.1     .16       0
  5182.1     .12       0  5281.8     .16       0    5773     .07       0
Bank Sta=4981.1,4999.1
XS Rating Curve= 0 ,0
Exp/Cntr=0.3,0.1

Type RM Length L Ch R = 1 ,5128    ,317,317,317
BEGIN DESCRIPTION:
624
END DESCRIPTION:
XS GIS Cut Line= 3
      1534349.29      6775684.21      1533502.94      6775475.88
      1532035.91      6775250.18
#Sta/Elev= 30
  4134.1 2087.62    4179 2088.96  4200.3 2084.33    4266 2083.31  4307.5 2077.38
  4375.4 2054.53  4428.6 2046.54  4473.5 2033.94  4478.7 2036.96  4509.3 2031.54
    4562 2029.72  4653.4 2022.45  4711.7 2021.73  4812.9 2022.29  4962.7 2020.46
  4963.2 2019.96  4980.7 2020.46  5236.3 2022.25  5624.6 2033.71    5985 2036.78
    6079 2045.11  6268.3 2052.52  6298.7 2055.72  6342.1 2068.17  6369.5 2085.06
  6405.3    2101  6410.4 2099.32  6430.2 2106.47  6468.5 2098.78    6490 2098.62
#Mann= 9 ,-1 , 0
  4134.1    .035       0    4179     .16       0  4428.6    .035       0
    4562     .16       0  4711.7     .07       0  4812.9     .16       0
  4962.7     .07       0  4980.7     .16       0  5624.6     .07       0
Bank Sta=4962.7,4980.7
XS Rating Curve= 0 ,0
Exp/Cntr=0.3,0.1

Type RM Length L Ch R = 1 ,4811    ,351,351,351
BEGIN DESCRIPTION:
623
END DESCRIPTION:
XS GIS Cut Line= 3
      1534557.64       6775467.2      1533459.54      6775202.44
      1532205.18      6775150.36
#Sta/Elev= 30
  3864.5 2085.92  3959.8 2084.93  4013.4  2073.5  4050.2 2077.46  4055.3 2074.18
  4118.3 2076.09  4155.2 2073.78  4186.2 2062.98  4222.9 2056.61  4344.8 2048.07
    4436 2030.31  4619.9  2021.1  4853.5 2019.65  4974.3 2019.31  4999.6 2016.81
  5000.1 2016.31  5017.7 2016.81  5228.8 2026.38  5746.4 2040.54  5879.4  2044.3
  5929.4 2039.64  5949.6    2043  5999.5  2039.3  6040.8 2040.35  6099.6 2041.42
  6149.6  2058.2  6190.2 2079.88  6209.6 2083.79  6238.6 2082.94  6249.5 2082.17
#Mann= 12 ,-1 , 0
  3864.5     .16       0  4118.3     .07       0  4344.8     .16       0
    4436    .035       0  4619.9     .16       0  4853.5     .12       0
  4974.3     .16       0  4999.6     .07       0  5017.7     .16       0
  5746.4     .07       0  6040.8    .035       0  6238.6     .07       0
Bank Sta=4999.6,5017.7
XS Rating Curve= 0 ,0
Exp/Cntr=0.3,0.1

Type RM Length L Ch R = 1 ,4460    ,254,254,254
BEGIN DESCRIPTION:
622
END DESCRIPTION:
XS GIS Cut Line= 3
      1534700.87       6775380.4      1533659.19        6774929.
      1532388.71      6774764.23
#Sta/Elev= 30
  3857.9 2079.92  3907.9 2077.34  3982.8 2081.45  4053.8 2079.92  4153.1 2054.18
  4200.1 2047.43  4205.5 2049.78  4223.6 2046.83    4229 2049.81  4252.6  2046.8
  4257.9 2048.18    4276 2043.62    4322 2049.38  4351.8  2045.4  4357.3 2047.82
  4409.7 2034.58  4451.2 2033.74  4515.6 2026.76  4526.4 2026.33  4735.9 2018.44
  4953.3 2017.53  4975.9 2016.75  4983.7 2012.93  4984.2 2012.43  5001.8 2012.93
  5017.6  2016.8  5209.2 2021.21  5289.8 2026.18  5818.3 2038.44  6274.3 2055.76
#Mann= 8 ,-1 , 0
  3857.9    .035       0  3982.8     .16       0  4252.6     .07       0
  4515.6     .16       0  4526.4    .035       0  4735.9     .16       0
  4983.7     .07       0  5001.8     .16       0
Bank Sta=4983.7,5001.8
XS Rating Curve= 0 ,0
Exp/Cntr=0.3,0.1

Type RM Length L Ch R = 1 ,4206    ,201,201,201
BEGIN DESCRIPTION:
10
END DESCRIPTION:
XS GIS Cut Line= 4
      1534650.23      6775273.77        1534355.        6775088.
      1533772.71       6774721.6      1532709.77      6774538.42
#Sta/Elev= 30
  3963.2 2070.58  4066.7  2067.3  4073.6 2070.06  4079.5 2066.31  4094.8 2075.27
  4100.7 2070.89  4110.1 2074.98    4116 2069.73  4131.3 2075.21  4186.9 2070.84
  4253.1 2074.99  4298.5 2075.85  4309.1  2069.4  4319.7  2070.3  4325.6 2063.75
    4335 2063.95  4340.9  2058.8    4442 2030.35    4514 2026.51  4563.4 2031.44
    4631 2020.86    4725 2017.69  4835.7 2016.14  4985.3 2012.87  4985.8 2012.37
  5003.4 2012.87  5110.3 2015.54  5785.1 2042.14  6032.2 2045.84  6078.6 2046.19
#Mann= 12 ,-1 , 0
  3963.2     .16       0  4066.7     .07       0  4186.9     .16       0
  4253.1     .07       0  4563.4    .035       0    4725     .16       0
  4835.7     .12       0  4985.3     .07       0  5003.4     .12       0
  5110.3     .16       0  5785.1     .07       0  6032.2     .16       0
Bank Sta=4985.3,5003.4
XS Rating Curve= 0 ,0
Exp/Cntr=0.3,0.1

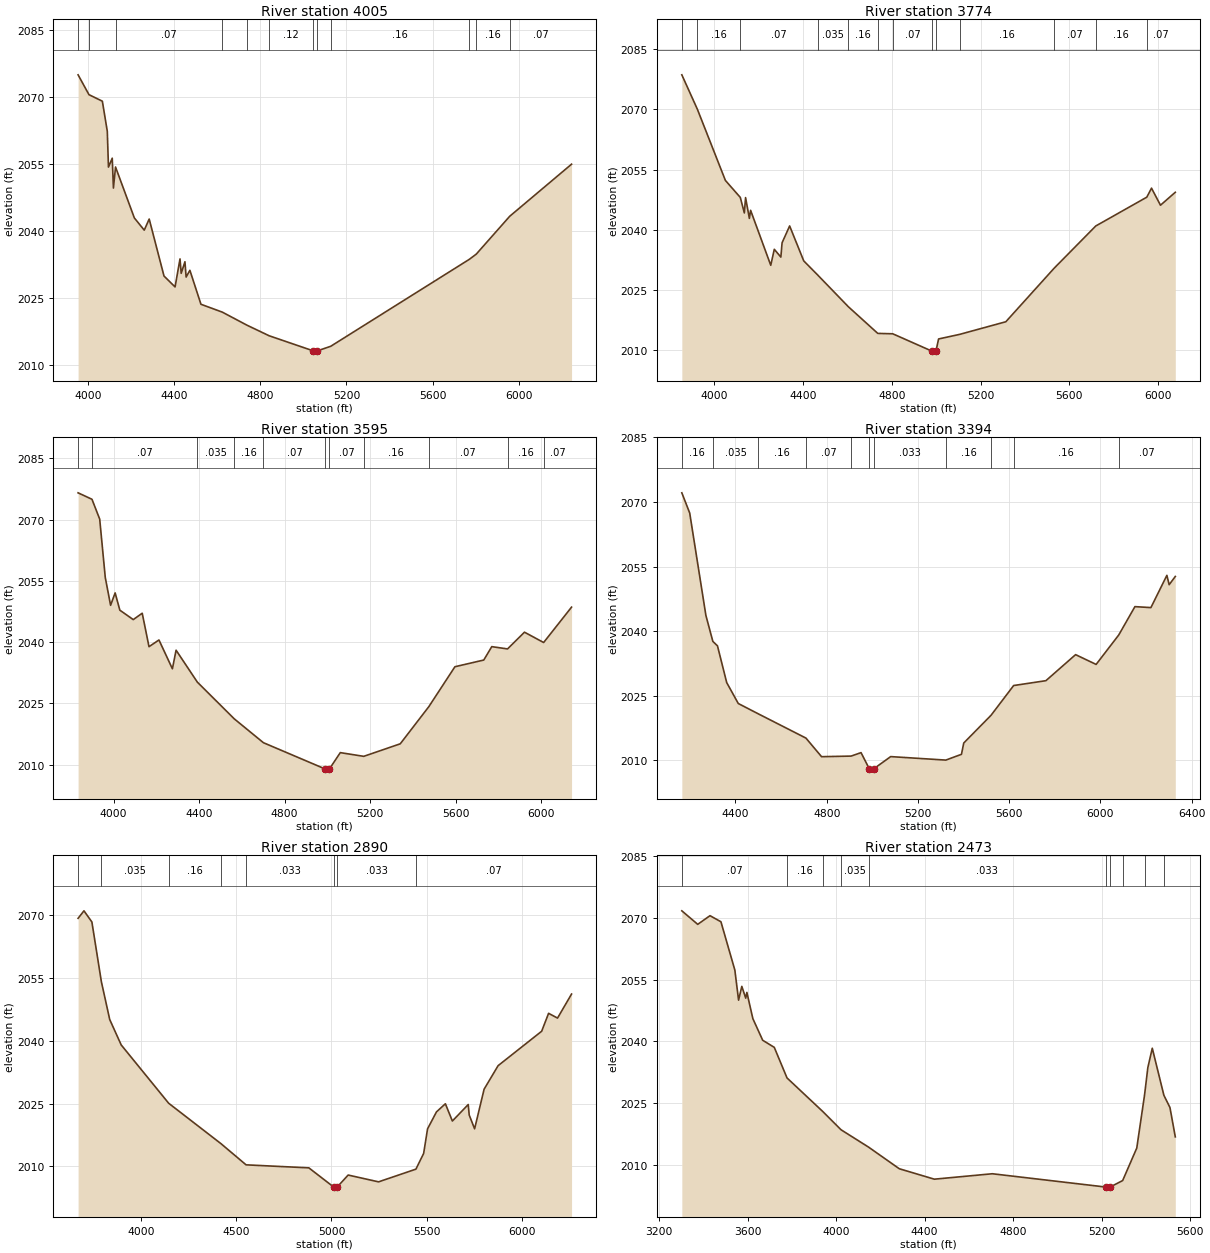
Type RM Length L Ch R = 1 ,4005    ,231,231,231
BEGIN DESCRIPTION:
621
END DESCRIPTION:
XS GIS Cut Line= 3
      1534839.75      6775011.47      1533889.23       6774573.1
      1532670.53      6774312.88
#Sta/Elev= 30
  3953.2 2074.89  4003.8 2070.45    4066 2068.99  4088.9 2062.26  4094.4 2054.25
  4111.9 2056.24  4117.4 2049.56  4127.2 2054.27  4214.7 2042.87  4260.6 2040.14
  4283.6 2042.63  4352.4 2029.88  4403.8 2027.44  4426.8 2033.71  4432.3 2030.48
  4449.7 2033.07  4455.2 2029.65  4472.7 2031.16  4524.1 2023.56  4623.4  2021.8
  4738.4 2018.87  4840.7 2016.52  5046.3 2013.13  5046.8 2012.63  5064.5 2013.13
  5127.1 2014.16  5770.4 2033.59  5803.4 2034.78  5958.9 2043.25  6246.1  2054.9
#Mann= 12 ,-1 , 0
  3953.2    .063       0  4003.8     .16       0  4127.2     .07       0
  4623.4    .035       0  4738.4     .16       0  4840.7     .12       0
  5046.3     .07       0  5064.5     .12       0  5127.1     .16       0
  5770.4     .07       0  5803.4     .16       0  5958.9     .07       0
Bank Sta=5046.3,5064.5
XS Rating Curve= 0 ,0
Exp/Cntr=0.3,0.1

Type RM Length L Ch R = 1 ,3774    ,179,179,179
BEGIN DESCRIPTION:
9
END DESCRIPTION:
XS GIS Cut Line= 4
      1534891.47      6774845.35        1534455.        6774638.
      1533855.52      6774353.22      1532788.87      6774200.01
#Sta/Elev= 30
  3853.1 2078.65  3923.2 2070.05  4049.5 2052.27  4116.6 2048.03  4134.9 2044.15
  4140.4 2047.98  4157.6 2042.79  4163.1 2044.81    4254 2031.07  4269.9 2035.07
  4299.5 2033.12    4305 2036.69  4339.1  2040.9  4402.7 2032.17  4465.6 2028.64
  4604.1  2020.7  4736.4 2014.06  4803.9 2013.96  4980.4 2009.63  4980.9 2009.13
  4998.6 2009.63  5010.6 2012.67  5105.2 2013.81  5313.7 2016.97  5531.6 2030.35
  5719.1 2040.89  5949.2 2048.09  5970.4 2050.34  6010.8 2046.08  6077.6 2049.31
#Mann= 13 ,-1 , 0
  3853.1    .035       0  3923.2     .16       0  4116.6     .07       0
  4465.6    .035       0  4604.1     .16       0  4736.4     .12       0
  4803.9     .07       0  4980.4     .07       0  4998.6     .07       0
  5105.2     .16       0  5531.6     .07       0  5719.1     .16       0
  5949.2     .07       0
Bank Sta=4980.4,4998.6
XS Rating Curve= 0 ,0
Exp/Cntr=0.3,0.1

Type RM Length L Ch R = 1 ,3595    ,201,201,201
BEGIN DESCRIPTION:
620
END DESCRIPTION:
XS GIS Cut Line= 3
      1535009.05      6774564.43      1533897.91      6774186.82
      1532765.13      6774121.71
#Sta/Elev= 30
  3833.9 2076.55  3898.9 2074.97    3935 2070.11  3961.1 2055.81    3986 2049.01
  4007.2 2052.05  4029.2 2047.82    4092 2045.51  4133.9 2047.07  4165.6 2038.88
  4212.2 2040.52    4275 2033.47  4292.3 2038.02  4391.8  2030.2  4563.8 2021.24
  4700.8 2015.37  4990.9 2008.91  4991.4 2008.41  5009.1 2008.91  5060.4 2012.94
  5170.1 2012.03  5340.9  2015.1  5474.6  2024.2  5596.6 2033.97  5731.6 2035.61
  5768.9 2038.89  5842.7 2038.33  5921.9 2042.43  6011.5  2039.9  6142.1 2048.56
#Mann= 11 ,-1 , 0
  3833.9    .035       0  3898.9     .07       0  4391.8    .035       0
  4563.8     .16       0  4700.8     .07       0  4990.9     .07       0
  5009.1     .07       0  5170.1     .16       0  5474.6     .07       0
  5842.7     .16       0  6011.5     .07       0
Bank Sta=4990.9,5009.1
XS Rating Curve= 0 ,0
Exp/Cntr=0.3,0.1

Type RM Length L Ch R = 1 ,3394    ,504,504,504
BEGIN DESCRIPTION:
619
END DESCRIPTION:
XS GIS Cut Line= 3
        1534779.      6774143.42      1533958.67      6774004.52
      1532628.13       6774052.2
#Sta/Elev= 30
  4164.9  2072.1  4199.4 2067.42  4270.4 2043.65  4300.9 2037.62  4321.1  2036.6
  4361.7 2028.06  4412.4 2023.21  4499.6 2020.83  4708.9 2015.19  4777.5 2010.87
    4907 2011.01  4950.6 2011.81  4987.1 2008.02  4987.6 2007.52  5005.3 2008.02
  5080.6 2010.89  5322.2 2010.08  5390.8 2011.42  5400.8 2014.04  5520.5 2020.48
  5619.6 2027.38  5761.1 2028.51  5891.2 2034.55  5981.2 2032.28  6080.5 2039.12
  6151.3 2045.69  6221.4 2045.47  6291.4 2052.95  6301.4 2050.78  6328.3 2052.69
#Mann= 11 ,-1 , 0
  4164.9     .16       0  4300.9    .035       0  4499.6     .16       0
  4708.9     .07       0    4907    .033       0  4987.1    .033       0
  5005.3    .033       0  5322.2     .16       0  5520.5     .07       0
  5619.6     .16       0  6080.5     .07       0
Bank Sta=4987.1,5005.3
XS Rating Curve= 0 ,0
Exp/Cntr=0.3,0.1

Type RM Length L Ch R = 1 ,2890    ,417,417,417
BEGIN DESCRIPTION:
618
END DESCRIPTION:
XS GIS Cut Line= 3
      1535234.75      6773896.03      1533958.67      6773531.43
      1532730.39      6773830.91
#Sta/Elev= 30
  3669.5 2069.32  3700.4 2071.11    3742 2068.44  3791.7 2054.18  3835.6 2045.11
  3895.9 2039.03  4145.1 2025.08  4419.8 2015.41  4551.7 2010.34  4881.3 2009.62
  5011.9 2005.03  5012.4 2004.53  5030.1 2005.03  5087.8  2007.9  5247.4 2006.27
  5443.6 2009.31  5484.2 2013.07  5504.7 2018.95  5551.6 2023.01  5598.4 2024.95
    5635 2020.82  5718.3 2024.77  5723.5 2022.25  5751.8 2018.96  5801.7 2028.44
  5875.3 2034.07  6103.9  2042.3  6140.4 2046.59  6187.3 2045.45  6260.9  2051.2
#Mann= 8 ,-1 , 0
  3669.5     .16       0  3791.7    .035       0  4145.1     .16       0
  4419.8     .07       0  4551.7    .033       0  5011.9    .033       0
  5030.1    .033       0  5443.6     .07       0
Bank Sta=5011.9,5030.1
XS Rating Curve= 0 ,0
Exp/Cntr=0.3,0.1

Type RM Length L Ch R = 1 ,2473    ,179,179,179
BEGIN DESCRIPTION:
617
END DESCRIPTION:
XS GIS Cut Line= 3
      1535373.56      6773700.69       1533767.7      6773192.89
      1533220.86      6773188.55
#Sta/Elev= 30
  3302.2 2071.78  3374.1 2068.49  3429.5  2070.6    3479 2069.12  3541.9 2057.37
  3558.8 2050.05  3573.4  2053.4  3591.1 2050.53  3596.3 2051.93  3623.4 2045.54
  3667.8 2040.29  3720.2 2038.56  3777.8 2031.12  3940.7 2022.89  4022.1 2018.51
  4146.8 2014.28  4285.4 2009.03  4443.9 2006.49  4706.1 2007.81    5220 2004.57
  5220.5 2004.07  5238.2 2004.57  5295.3 2006.15  5359.1 2014.06  5394.2 2026.93
  5409.2 2033.64  5429.2 2038.35  5481.7 2026.91  5509.2 2023.91  5533.3 2016.79
#Mann= 10 ,-1 , 0
  3302.2     .07       0  3777.8     .16       0  3940.7     .07       0
  4022.1    .035       0  4146.8    .033       0    5220    .033       0
  5238.2    .033       0  5295.3    .035       0  5394.2     .16       0
  5481.7     .07       0
Bank Sta=5220,5238.2
XS Rating Curve= 0 ,0
Exp/Cntr=0.3,0.1