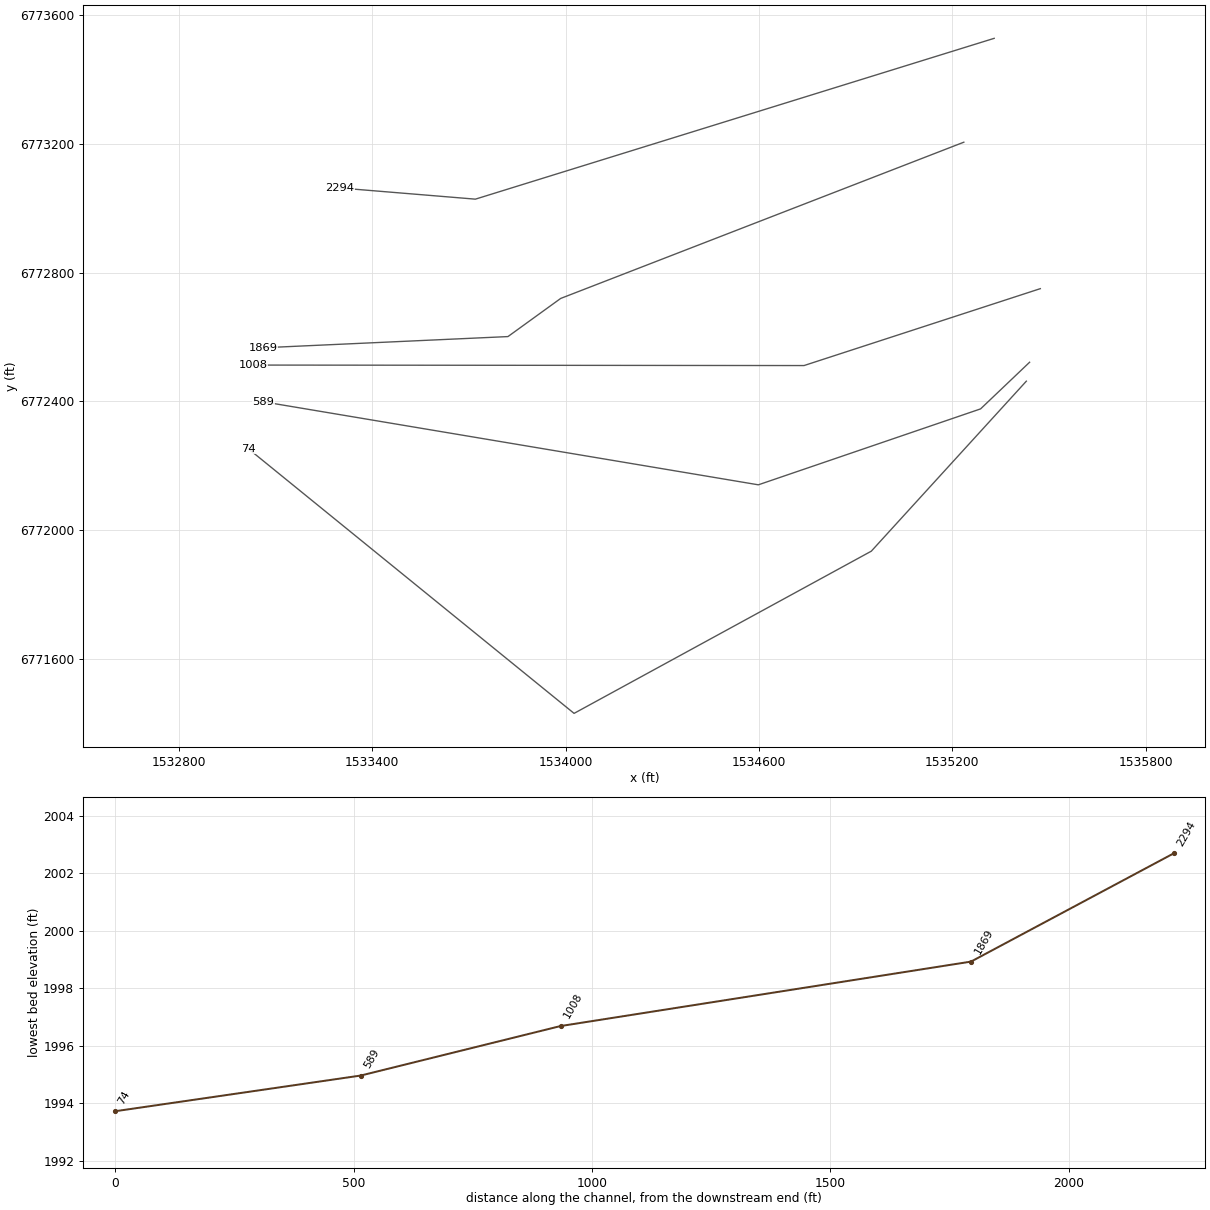
HEC-RAS study Elm 85.prj: Elm 85 Base Level Engineering

--- Elm 85.g01 (geometry) --- (continued)

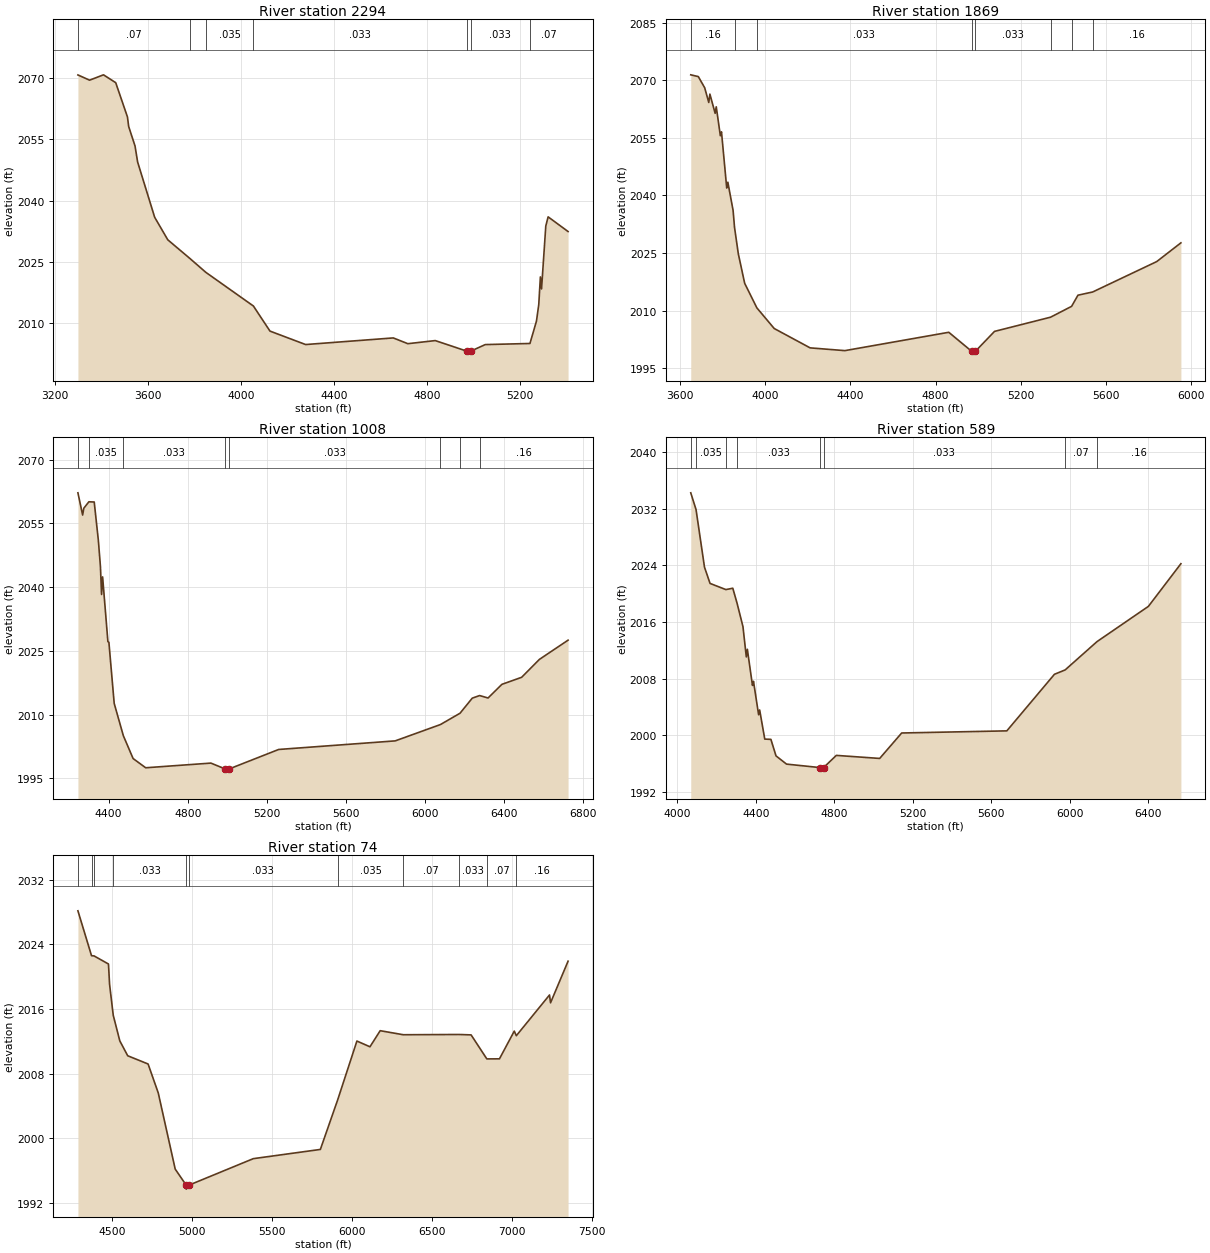
Type RM Length L Ch R = 1 ,2294    ,425,425,425
BEGIN DESCRIPTION:
616
END DESCRIPTION:
XS GIS Cut Line= 3
      1535330.21       6773527.1      1533719.96      6773027.96
      1533299.52      6773062.64
#Sta/Elev= 30
  3298.7 2070.77  3348.8 2069.49  3408.7  2070.8  3461.2 2068.88  3511.7 2060.49
    3517 2058.14  3544.3 2053.38  3555.4 2049.47  3628.7 2035.94  3685.2 2030.42
  3779.5 2025.89    3849 2022.45  4053.3 2014.22  4124.6 2008.08  4277.8 2004.79
  4654.7 2006.41  4717.5    2005  4835.2 2005.76  4970.2 2003.19  4970.7 2002.69
  4988.4 2003.19  5050.3 2004.78  5242.5 2005.05  5270.5 2010.53  5280.5 2014.63
  5287.3 2021.34  5292.3  2018.4  5310.6 2033.79  5320.6 2036.04  5406.4 2032.45
#Mann= 7 ,-1 , 0
  3298.7     .07       0  3779.5     .16       0    3849    .035       0
  4053.3    .033       0  4970.2    .033       0  4988.4    .033       0
  5242.5     .07       0
Bank Sta=4970.2,4988.4
XS Rating Curve= 0 ,0
Exp/Cntr=0.3,0.1

Type RM Length L Ch R = 1 ,1869    ,861,861,861
BEGIN DESCRIPTION:
615
END DESCRIPTION:
XS GIS Cut Line= 4
      1535235.99      6773204.73      1533984.71       6772719.8
      1533821.03      6772601.42      1533061.49       6772566.7
#Sta/Elev= 30
  3649.3 2071.43  3684.8 2070.97  3714.8 2068.06    3734 2064.23  3739.3 2066.41
  3763.9 2061.41  3769.2  2063.1  3788.4 2055.57  3793.8 2056.58  3818.4 2041.93
  3823.7 2043.45  3848.3 2036.12  3855.1 2031.68  3872.8 2024.83  3902.8 2017.12
  3960.1 2010.72  4041.7 2005.34  4210.5  2000.3  4373.9 1999.58  4862.3 2004.36
  4969.5 1999.43    4970 1998.93  4987.8 1999.43  5077.3 2004.59  5340.9 2008.29
  5439.8 2011.12  5469.6 2014.02  5538.8 2014.86    5840 2022.78  5953.6 2027.66
#Mann= 8 ,-1 , 0
  3649.3     .16       0  3855.1     .07       0  3960.1    .033       0
  4969.5    .033       0  4987.8    .033       0  5340.9    .035       0
  5439.8     .07       0  5538.8     .16       0
Bank Sta=4969.5,4987.8
XS Rating Curve= 0 ,0
Exp/Cntr=0.3,0.1

Type RM Length L Ch R = 1 ,1008    ,419,419,419
BEGIN DESCRIPTION:
614
END DESCRIPTION:
XS GIS Cut Line= 3
      1535473.43      6772750.19      1534739.92      6772511.47
        1533030.        6772513.
#Sta/Elev= 30
  4244.3 2062.21  4268.2 2056.98  4274.2 2058.59  4299.8  2060.1  4326.8 2060.05
  4347.8    2051  4358.3 2044.82    4364 2038.28  4369.3 2042.42    4396  2027.2
  4401.2    2027  4427.9 2012.64  4474.3 2005.02  4523.7 1999.65  4587.5 1997.48
  4917.4 1998.58  4990.7 1997.19  4991.2 1996.69    5009 1997.19  5260.6 2001.79
  5850.6 2003.81  6079.7 2007.66  6178.7 2010.32  6240.6 2013.87  6277.7 2014.48
  6320.6 2013.91  6390.6 2017.12  6490.6 2018.78  6580.6    2023  6725.6 2027.52
#Mann= 8 ,-1 , 0
  4244.3     .07       0  4299.8    .035       0  4474.3    .033       0
  4990.7    .033       0    5009    .033       0  6079.7    .035       0
  6178.7     .07       0  6277.7     .16       0
Bank Sta=4990.7,5009
XS Rating Curve= 0 ,0
Exp/Cntr=0.3,0.1

Type RM Length L Ch R = 1 ,589     ,515,515,515
BEGIN DESCRIPTION:
802
END DESCRIPTION:
XS GIS Cut Line= 4
      1535440.12      6772521.77      1535287.97      6772376.98
       1534598.2      6772141.33      1533061.61      6772399.07
#Sta/Elev= 30
  4068.5 2034.23  4095.4 2031.87  4138.5 2023.74  4166.8 2021.45  4247.4 2020.58
  4282.7 2020.77  4304.5 2018.65  4334.5 2015.35  4351.5 2011.08  4356.8 2012.16
  4382.9 2007.06  4388.1 2007.64  4414.2 2002.92  4419.5  2003.6  4445.5 1999.49
  4476.8 1999.45  4502.8 1997.12  4556.4 1995.96  4726.9 1995.47  4727.4 1994.97
  4745.2 1995.47    4810 1997.19    5031 1996.76    5143 2000.35  5678.7 2000.65
  5921.2 2008.63  5975.9 2009.25  6138.1 2013.24  6399.8 2018.21  6565.5 2024.23
#Mann= 8 ,-1 , 0
  4068.5     .07       0  4095.4    .035       0  4247.4     .07       0
  4304.5    .033       0  4726.9    .033       0  4745.2    .033       0
  5975.9     .07       0  6138.1     .16       0
Bank Sta=4726.9,4745.2
XS Rating Curve= 0 ,0
Exp/Cntr=0.3,0.1

Type RM Length L Ch R = 1 ,74      ,0,0,0
BEGIN DESCRIPTION:
8
END DESCRIPTION:
XS GIS Cut Line= 4
        1535430.        6772463.      1534948.89      6771935.42
      1534026.27      6771431.93      1533015.78      6772252.88
#Sta/Elev= 30
    4286 2028.16  4371.1 2022.61  4387.1 2022.58  4477.2 2021.58    4484 2019.08
    4507 2015.24  4548.1 2012.07  4597.5 2010.23  4725.1 2009.21  4788.7 2005.63
  4894.7 1996.21  4963.2 1994.23  4963.7 1993.73  4981.7 1994.23  5383.4  1997.5
    5803 1998.64  5911.3 2004.77  6031.7 2012.05  6113.4 2011.34  6177.4 2013.33
  6322.1 2012.83  6670.4 2012.86  6746.3 2012.81  6844.7 2009.84  6923.7 2009.85
  7016.4 2013.28  7029.3 2012.71  7236.9 2017.75  7243.3 2016.78    7353 2021.93
#Mann= 11 ,-1 , 0
    4286    .035       0  4371.1    .033       0  4387.1     .07       0
    4507    .033       0  4963.2    .033       0  4981.7    .033       0
  5911.3    .035       0  6322.1     .07       0  6670.4    .033       0
  6844.7     .07       0  7029.3     .16       0
Bank Sta=4963.2,4981.7
XS Rating Curve= 0 ,0
Exp/Cntr=0.3,0.1

Chan Stop Cuts=-1
Use User Specified Reach Order=0
Composite Channel Slope=5