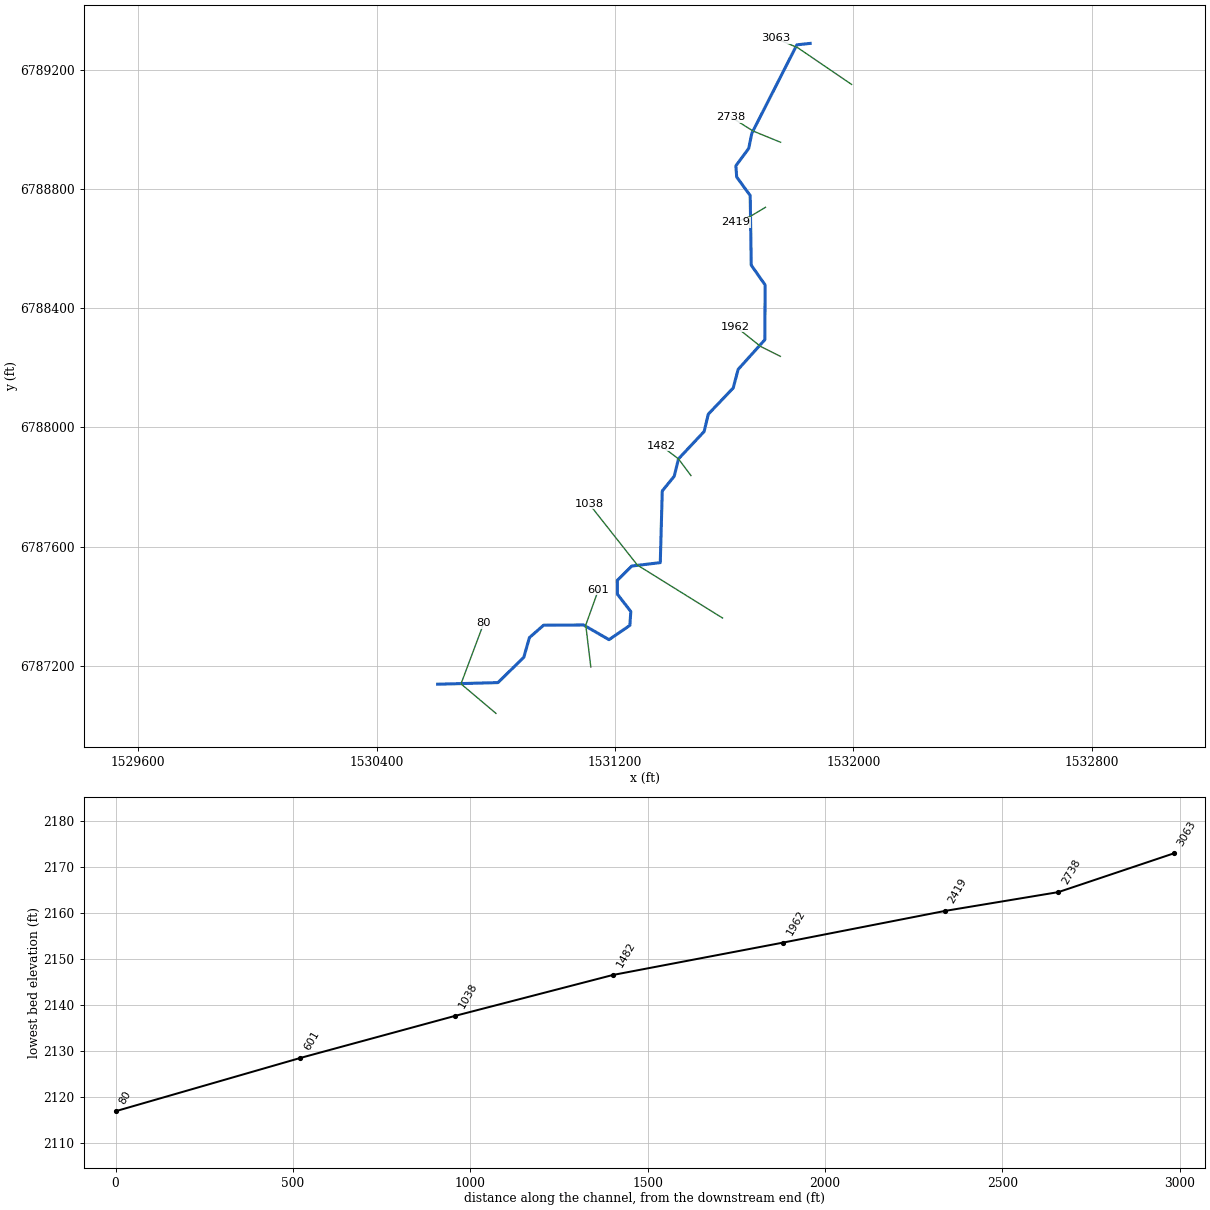
--- Elm 86.prj (project) ---

Proj Title=Elm 86 Base Level Engineering
Current Plan=p01
Default Exp/Contr=0.3,0.1
English Units
Geom File=g01
Flow File=f01
Plan File=p01
BEGIN DESCRIPTION:
Elm 86
END DESCRIPTION:

--- Elm 86.p01 (plan) ---

Plan Title=Multiple Run
Short Identifier=Multiple
Geom File=g01
Flow File=f01
Subcritical Flow
K Sum by GR= 0
Std Step Tol= 0.01
Critical Tol= 0.01
Num of Std Step Trials= 20
Max Error Tol= 0.3
Flow Tol Ratio= 0.001
Split Flow NTrial= 30
Split Flow Tol= 0.02
Split Flow Ratio= 0.02
Log Output Level= 0
Friction Slope Method= 1
Unsteady Friction Slope Method= 2
Unsteady Bridges Friction Slope Method= 1
Parabolic Critical Depth
Global Vel Dist=  1 , 1 , 1
Global Log Level= 0
CheckData=True
Encroach Param= -1, 0, 0, 0
BEGIN DESCRIPTION:
Multiple Run
END DESCRIPTION:

--- Elm 86.f01 (steady flow) ---

Flow Title=Multiple
Number of Profiles=7
Profile Names=10-year,25-year,50-year,1pct_min,100-year,1pct_plu,500-year
River Rch & RM= Elm 86,Reach-1,3063
     281     398     496     385     618     850     967
Boundary for River Rch & Prof#=Elm 86,Reach-1,1
Up Type=0
Dn Type=3
Dn Slope=0.005
Boundary for River Rch & Prof#=Elm 86,Reach-1,2
Up Type=0
Dn Type=3
Dn Slope=0.005
Boundary for River Rch & Prof#=Elm 86,Reach-1,3
Up Type=0
Dn Type=3
Dn Slope=0.005
Boundary for River Rch & Prof#=Elm 86,Reach-1,4
Up Type=0
Dn Type=3
Dn Slope=0.005
Boundary for River Rch & Prof#=Elm 86,Reach-1,5
Up Type=0
Dn Type=3
Dn Slope=0.005
Boundary for River Rch & Prof#=Elm 86,Reach-1,6
Up Type=0
Dn Type=3
Dn Slope=0.005
Boundary for River Rch & Prof#=Elm 86,Reach-1,7
Up Type=0
Dn Type=3
Dn Slope=0.005

--- Elm 86.g01 (geometry) ---

Geom Title=Existing Conditions

River Reach=Elm 86,Reach-1
Reach XY= 30
      1531855.00      6789288.00      1531810.28      6789283.10
      1531659.16      6788986.28      1531648.84      6788935.80
      1531605.75      6788877.32      1531608.37      6788839.74
      1531653.76      6788777.50      1531657.26      6788543.94
      1531703.78      6788477.49      1531702.94      6788293.86
      1531613.18      6788194.04      1531596.82      6788131.96
      1531513.18      6788044.04      1531499.13      6787985.72
      1531413.16      6787894.05      1531398.86      6787835.83
      1531358.75      6787786.45      1531352.06      6787545.97
      1531256.30      6787534.44      1531208.03      6787486.61
      1531208.36      6787439.77      1531253.21      6787381.83
      1531250.01      6787335.38      1531180.14      6787287.47
      1531094.50      6787336.77      1530960.68      6787336.03
      1530913.02      6787294.38      1530894.22      6787228.32
      1530807.47      6787143.45      1530605.00      6787138.00

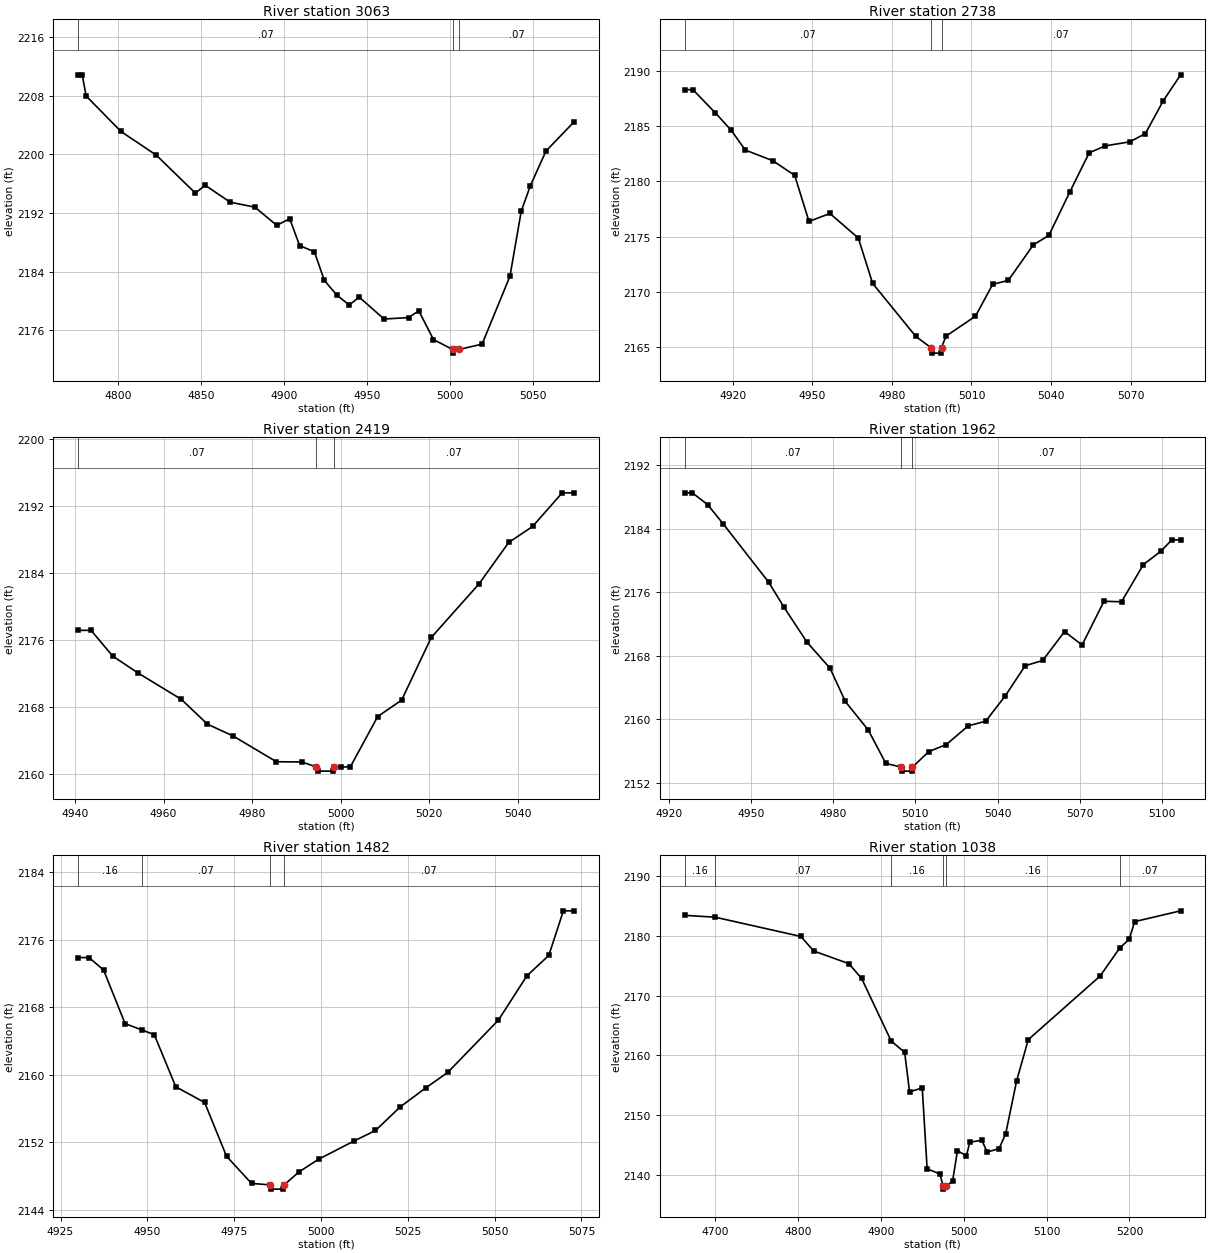
Type RM Length L Ch R = 1,3063,325,325,325
BEGIN DESCRIPTION:
391
END DESCRIPTION:
XS GIS Cut Line= 3
      1531993.95      6789150.28      1531813.10      6789273.53
      1531739.37      6789304.94
#Sta/Elev= 30
  4776.1 2210.83  4778.5 2210.83  4780.9 2207.94  4801.9 2203.10  4823.2 2199.87
  4846.7 2194.70  4852.7 2195.76  4867.7 2193.46  4882.6 2192.78  4895.8 2190.30
  4903.6 2191.20  4909.6 2187.54  4918.5 2186.69  4924.5 2182.78  4932.2 2180.74
  4939.5 2179.44  4945.5 2180.51  4960.5 2177.52  4975.4 2177.72  4981.4 2178.65
  4990.3 2174.72  5001.8 2173.37  5002.0 2172.87  5005.8 2173.37  5019.6 2174.10
  5036.4 2183.36  5043.2 2192.23  5048.7 2195.71  5058.1 2200.43  5075.1 2204.43
#Mann=3,-1,0
  4776.1    0.07       0  5001.8    0.07       0  5005.8    0.07       0
Bank Sta=5001.8,5005.8
Exp/Cntr=0.3,0.1

Type RM Length L Ch R = 1,2738,319,319,319
BEGIN DESCRIPTION:
808
END DESCRIPTION:
XS GIS Cut Line= 3
      1531755.75      6788956.22      1531663.26      6788994.00
      1531589.54      6789040.56
#Sta/Elev= 29
  4901.8 2188.29  4904.9 2188.29  4913.4 2186.18  4919.3 2184.63  4924.7 2182.82
  4935.0 2181.87  4943.3 2180.54  4948.7 2176.37  4956.6 2177.09  4967.3 2174.87
  4972.7 2170.77  4989.0 2165.97  4994.7 2164.96  4995.0 2164.46  4998.5 2164.46
  4998.7 2164.96  5000.4 2166.00  5011.5 2167.80  5018.0 2170.68  5023.9 2171.04
  5033.3 2174.24  5039.2 2175.11  5047.0 2178.99  5054.4 2182.57  5060.4 2183.20
  5069.7 2183.57  5075.6 2184.31  5082.4 2187.30  5088.9 2189.63
#Mann=3,-1,0
  4901.8    0.07       0  4994.7    0.07       0  4998.7    0.07       0
Bank Sta=4994.7,4998.7
Exp/Cntr=0.3,0.1

Type RM Length L Ch R = 1,2419,457,457,457
BEGIN DESCRIPTION:
390
END DESCRIPTION:
XS GIS Cut Line= 3
      1531704.99      6788737.99      1531654.06      6788707.62
      1531605.03      6788688.01
#Sta/Elev= 23
  4940.7 2177.16  4943.6 2177.16  4948.5 2174.09  4954.3 2172.05  4964.0 2168.94
  4969.9 2165.98  4975.7 2164.57  4985.5 2161.50  4991.3 2161.47  4994.5 2160.88
  4994.8 2160.38  4998.3 2160.38  4998.5 2160.88  5000.0 2160.88  5002.2 2160.88
  5008.4 2166.89  5013.8 2168.84  5020.5 2176.31  5031.3 2182.70  5038.0 2187.63
  5043.4 2189.54  5050.1 2193.55  5052.8 2193.55
#Mann=3,-1,0
  4940.7    0.07       0  4994.5    0.07       0  4998.5    0.07       0
Bank Sta=4994.5,4998.5
Exp/Cntr=0.3,0.1

Type RM Length L Ch R = 1,1962,480,480,480
BEGIN DESCRIPTION:
389
END DESCRIPTION:
XS GIS Cut Line= 3
      1531754.99      6788238.01      1531688.54      6788271.25
      1531605.02      6788337.98
#Sta/Elev= 30
  4925.7 2188.53  4928.5 2188.53  4934.1 2187.04  4939.7 2184.65  4956.4 2177.27
  4962.0 2174.12  4970.4 2169.72  4978.8 2166.45  4984.4 2162.26  4992.8 2158.65
  4999.2 2154.46  5004.9 2153.99  5005.1 2153.49  5008.6 2153.49  5008.9 2153.99
  5014.9 2155.95  5021.3 2156.84  5029.3 2159.19  5035.7 2159.78  5042.9 2163.00
  5050.1 2166.76  5056.5 2167.42  5064.5 2171.06  5070.9 2169.37  5078.9 2174.88
  5085.3 2174.81  5093.3 2179.50  5099.7 2181.18  5103.7 2182.61  5106.9 2182.61
#Mann=3,-1,0
  4925.7    0.07       0  5004.9    0.07       0  5008.9    0.07       0
Bank Sta=5004.9,5008.9
Exp/Cntr=0.3,0.1

Type RM Length L Ch R = 1,1482,444,444,444
BEGIN DESCRIPTION:
388
END DESCRIPTION:
XS GIS Cut Line= 3
      1531454.97      6787838.04      1531413.16      6787894.05
      1531355.00      6787938.00
#Sta/Elev= 26
  4930.1 2173.90  4933.2 2173.90  4937.4 2172.43  4943.6 2166.07  4948.5 2165.31
  4952.0 2164.76  4958.2 2158.58  4966.5 2156.72  4972.8 2150.35  4980.0 2147.13
  4985.4 2146.95  4985.6 2146.45  4989.1 2146.45  4989.4 2146.95  4993.6 2148.47
  4999.3 2149.99  5009.4 2152.13  5015.7 2153.40  5022.8 2156.19  5030.2 2158.46
  5036.5 2160.28  5051.1 2166.49  5059.3 2171.74  5065.6 2174.15  5069.8 2179.44
  5072.9 2179.44
#Mann=4,-1,0
  4930.1    0.16       0  4948.5    0.07       0  4985.4    0.07       0
  4989.4    0.07       0
Bank Sta=4985.4,4989.4
Exp/Cntr=0.3,0.1

Type RM Length L Ch R = 1,1038,437,437,437
BEGIN DESCRIPTION:
387
END DESCRIPTION:
XS GIS Cut Line= 3
      1531560.95      6787360.09      1531275.10      6787537.84
      1531113.09      6787743.36
#Sta/Elev= 30
  4663.4 2183.48  4700.3 2183.17  4803.6 2179.94  4819.0 2177.51  4861.5 2175.38
  4876.8 2172.92  4912.5 2162.42  4928.8 2160.50  4934.7 2153.90  4950.0 2154.54
  4955.9 2140.99  4971.3 2140.12  4975.2 2138.08  4975.4 2137.58  4979.2 2138.08
  4986.6 2138.94  4992.5 2144.02  5003.3 2143.18  5007.4 2145.45  5021.9 2145.78
  5028.2 2143.80  5042.7 2144.37  5050.7 2146.88  5063.9 2155.76  5077.9 2162.64
  5164.6 2173.31  5188.0 2177.96  5199.8 2179.50  5206.2 2182.43  5261.7 2184.24
#Mann=6,-1,0
  4663.4    0.16       0  4700.3    0.07       0  4912.5    0.16       0
  4975.2    0.07       0  4979.2    0.16       0  5188.0    0.07       0
Bank Sta=4975.2,4979.2
Exp/Cntr=0.3,0.1

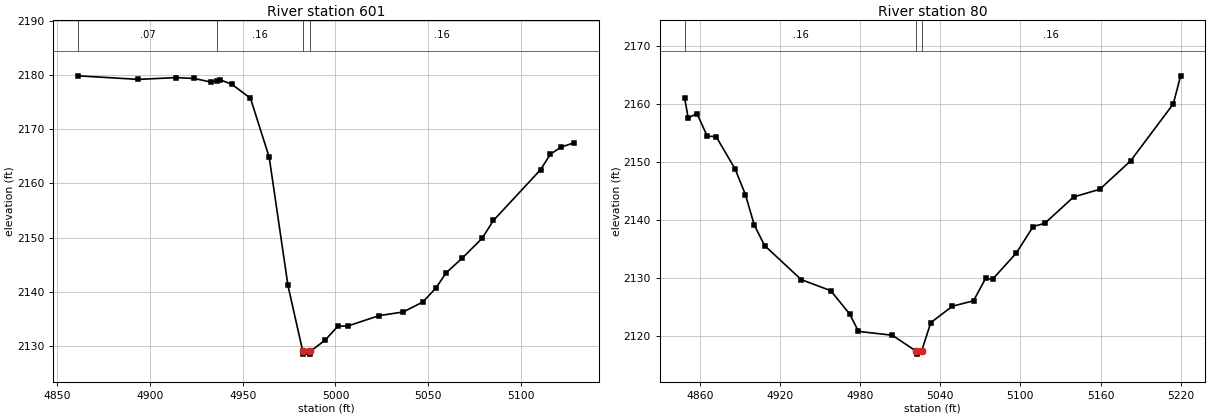
Type RM Length L Ch R = 1,601,521,521,521
BEGIN DESCRIPTION:
807
END DESCRIPTION:
XS GIS Cut Line= 3
      1531118.99      6787195.84      1531102.06      6787336.45
      1531144.46      6787454.65
#Sta/Elev= 30
  4861.4 2179.92  4893.8 2179.26  4913.9 2179.59  4924.0 2179.43  4932.8 2178.77
  4936.3 2179.05  4937.9 2179.18  4944.2 2178.35  4954.2 2175.77  4964.3 2164.85
  4974.4 2141.13  4982.4 2128.92  4982.7 2128.42  4986.2 2128.42  4986.4 2128.92
  4994.5 2131.02  5001.3 2133.61  5006.5 2133.61  5023.6 2135.55  5036.5 2136.22
  5047.2 2138.09  5054.3 2140.74  5059.6 2143.46  5068.4 2146.22  5079.0 2149.85
  5085.1 2153.15  5110.5 2162.55  5115.8 2165.42  5121.5 2166.72  5128.6 2167.54
#Mann=4,-1,0
  4861.4    0.07       0  4936.3    0.16       0  4982.4    0.07       0
  4986.4    0.16       0
Bank Sta=4982.4,4986.4
Exp/Cntr=0.3,0.1

Type RM Length L Ch R = 1,80,0,0,0
BEGIN DESCRIPTION:
386
END DESCRIPTION:
XS GIS Cut Line= 3
      1530800.71      6787040.18      1530683.53      6787139.12
      1530759.93      6787343.12
#Sta/Elev= 30
  4848.7 2161.01  4851.3 2157.61  4857.9 2158.34  4865.6 2154.44  4872.2 2154.39
  4886.5 2148.76  4894.2 2144.33  4900.8 2139.11  4908.5 2135.58  4935.9 2129.70
  4958.0 2127.79  4972.2 2123.76  4978.8 2120.76  5004.1 2120.10  5022.0 2117.34
  5022.3 2116.84  5026.0 2117.34  5032.9 2122.27  5049.0 2125.10  5064.9 2126.05
  5073.9 2129.89  5079.2 2129.78  5097.0 2134.30  5109.5 2138.85  5118.3 2139.42
  5139.8 2143.96  5159.4 2145.28  5182.4 2150.17  5214.4 2160.01  5219.9 2164.86
#Mann=3,-1,0
  4848.7    0.16       0  5022.0    0.07       0  5026.0    0.16       0
Bank Sta=5022,5026
Exp/Cntr=0.3,0.1

Chan Stop Cuts=-1