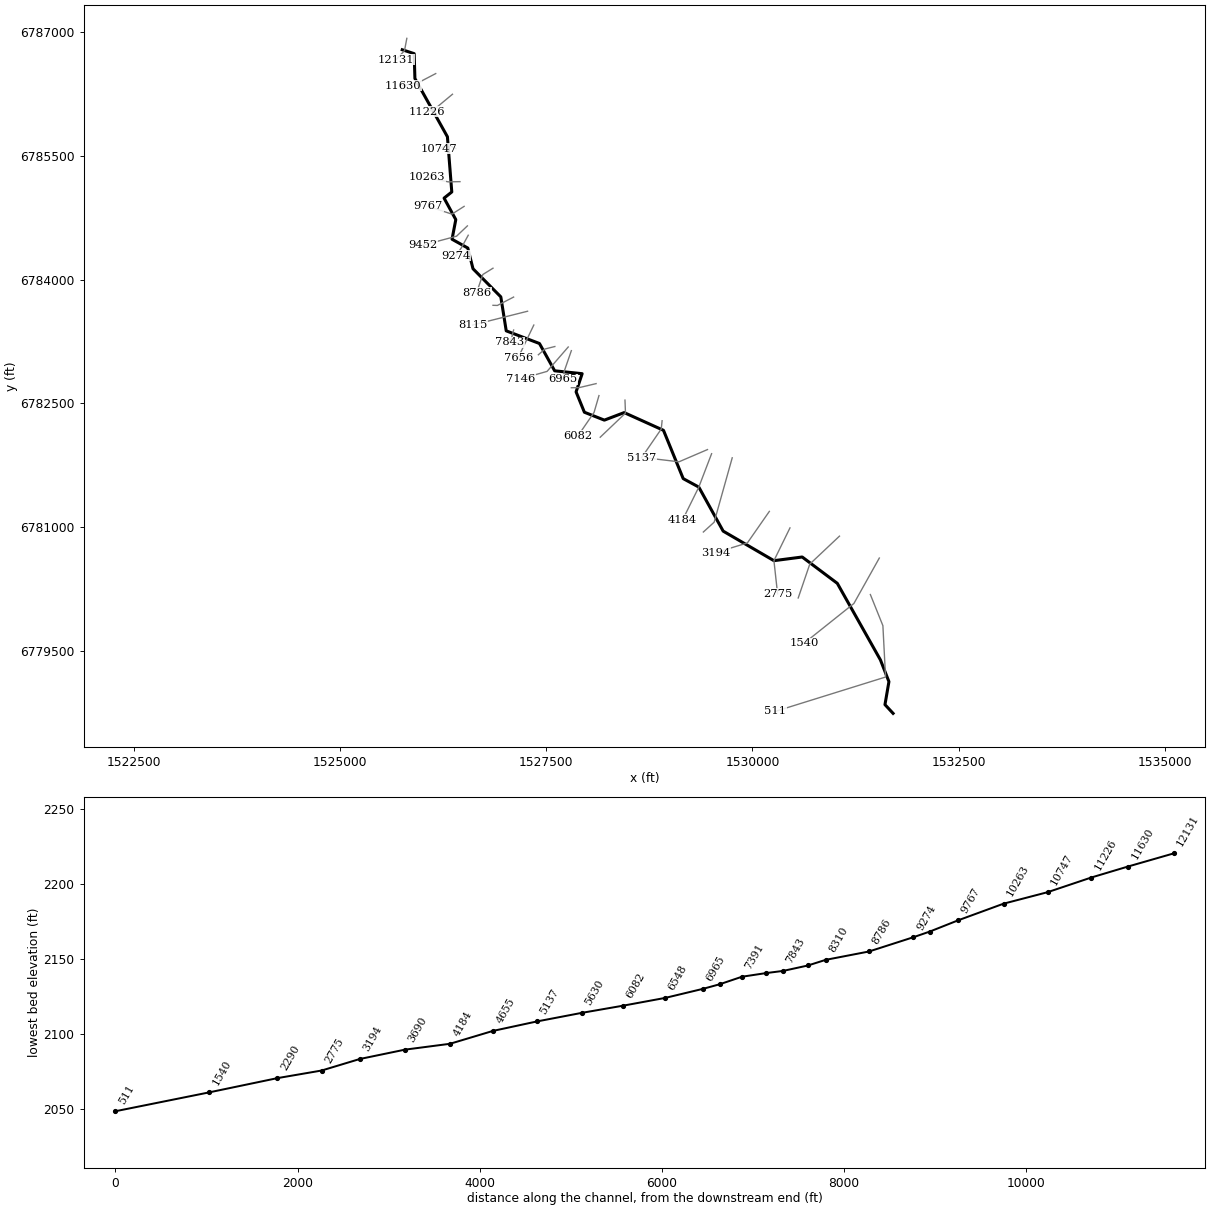
--- Elm 87.prj (project) ---

Proj Title=Elm 87 Base Level Engineering
Current Plan=p01
Default Exp/Contr=0.3,0.1
English Units
Geom File=g01
Flow File=f01
Plan File=p01
BEGIN DESCRIPTION:
Elm 87
END DESCRIPTION:

--- Elm 87.p01 (plan) ---

Plan Title=Multiple Run
Short Identifier=Multiple
Geom File=g01
Flow File=f01
Subcritical Flow
K Sum by GR= 0
Std Step Tol= 0.01
Critical Tol= 0.01
Num of Std Step Trials= 20
Max Error Tol= 0.3
Flow Tol Ratio= 0.001
Split Flow NTrial= 30
Split Flow Tol= 0.02
Split Flow Ratio= 0.02
Log Output Level= 0
Friction Slope Method= 1
Unsteady Friction Slope Method= 2
Unsteady Bridges Friction Slope Method= 1
Parabolic Critical Depth
Global Vel Dist=  1 , 1 , 1
Global Log Level= 0
CheckData=True
Encroach Param= -1, 0, 0, 0
BEGIN DESCRIPTION:
Multiple Run
END DESCRIPTION:

--- Elm 87.f01 (steady flow) ---

Flow Title=Multiple
Number of Profiles=7
Profile Names=10-year,25-year,50-year,1pct_min,100-year,1pct_plu,500-year
River Rch & RM= Elm 87,Reach-1,12131
     318     453     568     443     710     977    1120
River Rch & RM= Elm 87,Reach-1,6082
     487     709     903     713    1140    1570    1850
Boundary for River Rch & Prof#=Elm 87,Reach-1,1
Up Type=0
Dn Type=3
Dn Slope=0.005
Boundary for River Rch & Prof#=Elm 87,Reach-1,2
Up Type=0
Dn Type=3
Dn Slope=0.005
Boundary for River Rch & Prof#=Elm 87,Reach-1,3
Up Type=0
Dn Type=3
Dn Slope=0.005
Boundary for River Rch & Prof#=Elm 87,Reach-1,4
Up Type=0
Dn Type=3
Dn Slope=0.005
Boundary for River Rch & Prof#=Elm 87,Reach-1,5
Up Type=0
Dn Type=3
Dn Slope=0.005
Boundary for River Rch & Prof#=Elm 87,Reach-1,6
Up Type=0
Dn Type=3
Dn Slope=0.005
Boundary for River Rch & Prof#=Elm 87,Reach-1,7
Up Type=0
Dn Type=3
Dn Slope=0.005

--- Elm 87.g01 (geometry) ---

Geom Title=Existing Conditions

River Reach=Elm 87,Reach-1
Reach XY= 30
      1525755.00      6786788.00      1525899.68      6786740.73
      1525908.54      6786439.46      1526302.65      6785732.48
      1526355.51      6785062.88      1526262.03      6784988.21
      1526404.23      6784727.31      1526358.52      6784489.46
      1526549.56      6784382.75      1526612.70      6784131.53
      1526949.91      6783790.30      1527015.47      6783378.17
      1527418.35      6783224.64      1527602.53      6782893.45
      1527935.78      6782858.58      1527862.30      6782637.92
      1527962.92      6782390.92      1528205.00      6782295.10
      1528445.34      6782386.65      1528921.75      6782171.54
      1529160.80      6781585.70      1529349.89      6781482.89
      1529645.32      6780948.76      1530260.52      6780590.35
      1530603.37      6780634.87      1531028.89      6780315.28
      1531551.46      6779386.53      1531654.61      6779122.84
      1531606.56      6778844.03      1531705.00      6778738.00

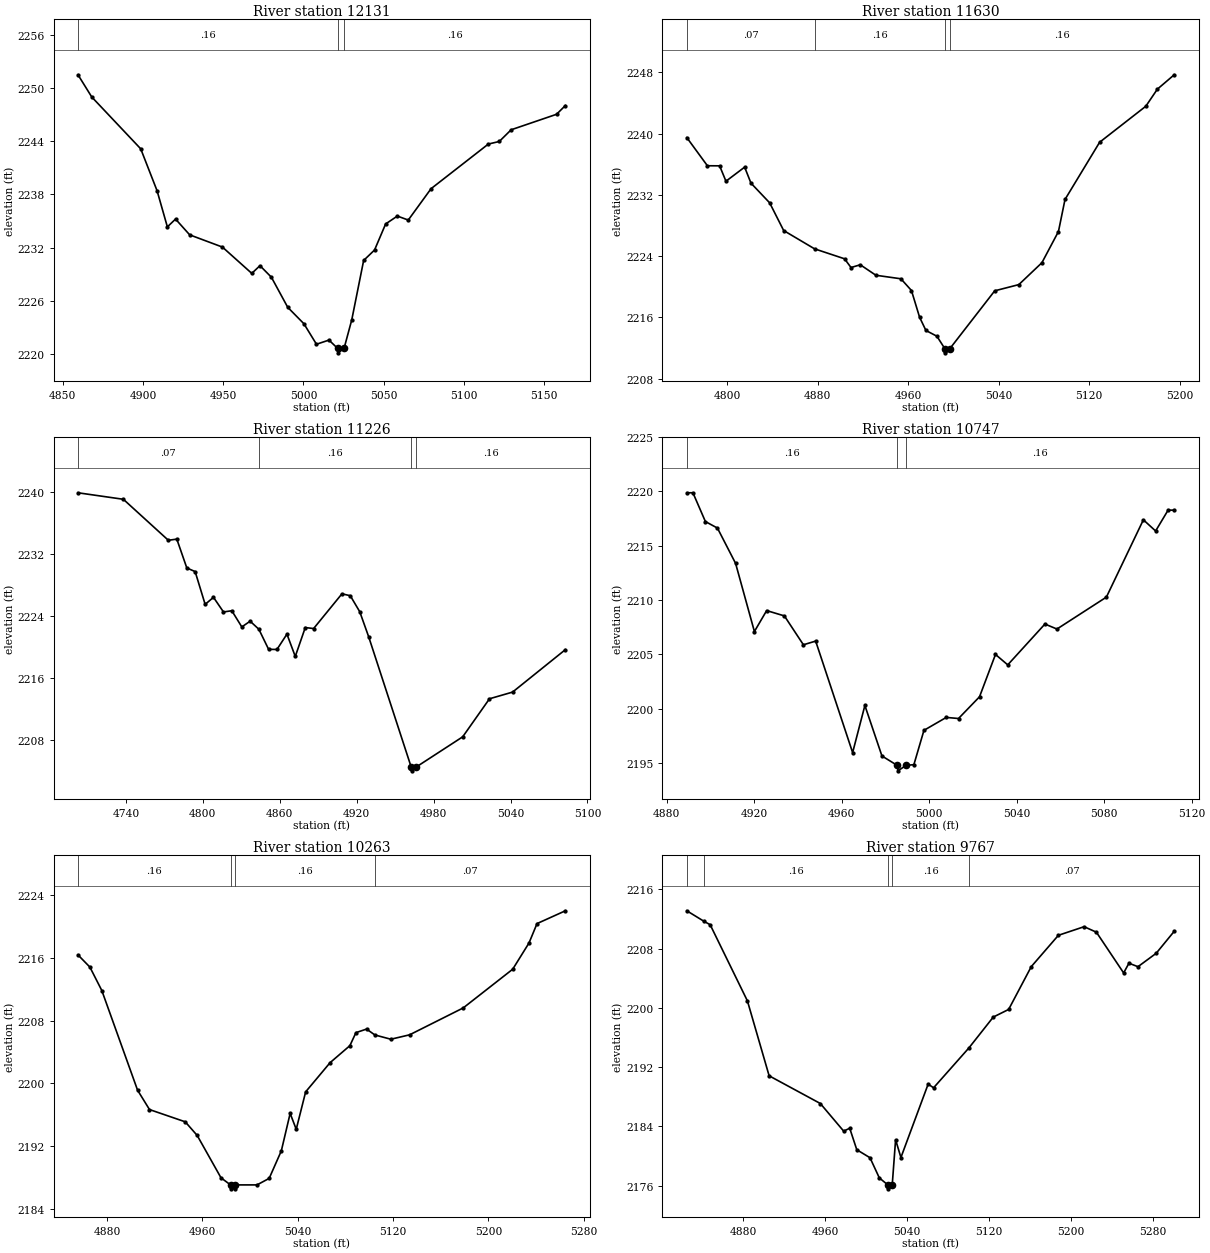
Type RM Length L Ch R = 1,12131,501,501,501
BEGIN DESCRIPTION:
270
END DESCRIPTION:
XS GIS Cut Line= 3
      1525810.54      6786926.42      1525782.64      6786777.73
      1525679.25      6786665.74
#Sta/Elev= 30
  4859.5 2251.51  4868.1 2249.00  4898.6 2243.15  4908.8 2238.41  4915.2 2234.34
  4920.3 2235.22  4929.1 2233.44  4949.5 2232.06  4967.8 2229.09  4972.9 2229.96
  4980.0 2228.66  4990.2 2225.26  5000.3 2223.40  5008.1 2221.09  5015.9 2221.56
  5021.3 2220.62  5021.6 2220.12  5025.3 2220.62  5030.1 2223.85  5037.5 2230.55
  5044.3 2231.73  5051.2 2234.67  5058.5 2235.56  5065.3 2235.11  5079.5 2238.65
  5115.2 2243.69  5122.0 2243.98  5129.4 2245.30  5157.7 2247.05  5163.2 2248.04
#Mann=3,-1,0
  4859.5    0.16       0  5021.3    0.07       0  5025.3    0.16       0
Bank Sta=5021.3,5025.3
Exp/Cntr=0.3,0.1

Type RM Length L Ch R = 1,11630,404,404,404
BEGIN DESCRIPTION:
806
END DESCRIPTION:
XS GIS Cut Line= 3
      1526160.91      6786498.93      1525955.64      6786391.71
      1525760.34      6786352.91
#Sta/Elev= 30
  4764.5 2239.49  4782.7 2235.81  4793.5 2235.80  4799.1 2233.79  4815.6 2235.63
  4821.2 2233.54  4837.7 2230.97  4850.1 2227.35  4877.4 2224.96  4903.9 2223.66
  4909.6 2222.52  4917.8 2222.88  4931.6 2221.51  4953.7 2221.05  4963.0 2219.52
  4970.2 2216.03  4975.8 2214.30  4985.5 2213.55  4992.7 2211.88  4992.9 2211.38
  4996.7 2211.88  5036.6 2219.48  5057.9 2220.29  5078.3 2223.15  5092.9 2227.22
  5098.7 2231.41  5129.3 2238.88  5170.1 2243.58  5180.3 2245.81  5195.2 2247.69
#Mann=4,-1,0
  4764.5    0.07       0  4877.4    0.16       0  4992.7    0.07       0
  4996.7    0.16       0
Bank Sta=4992.7,4996.7
Exp/Cntr=0.3,0.1

Type RM Length L Ch R = 1,11226,479,479,479
BEGIN DESCRIPTION:
269
END DESCRIPTION:
XS GIS Cut Line= 3
      1526363.92      6786248.39      1526135.33      6786058.14
      1526055.01      6786038.00
#Sta/Elev= 30
  4702.6 2239.92  4738.0 2239.08  4773.1 2233.79  4779.7 2233.94  4787.5 2230.22
  4794.0 2229.75  4801.8 2225.52  4808.3 2226.43  4816.1 2224.54  4822.6 2224.70
  4830.4 2222.61  4836.9 2223.35  4843.7 2222.31  4851.3 2219.72  4857.8 2219.70
  4865.6 2221.68  4872.1 2218.80  4879.9 2222.53  4886.4 2222.40  4908.5 2226.88
  4915.0 2226.64  4922.4 2224.57  4929.4 2221.32  4962.5 2204.54  4962.8 2204.04
  4966.5 2204.54  5002.7 2208.43  5023.6 2213.34  5041.6 2214.20  5082.8 2219.68
#Mann=4,-1,0
  4702.6    0.07       0  4843.7    0.16       0  4962.5    0.07       0
  4966.5    0.16       0
Bank Sta=4962.5,4966.5
Exp/Cntr=0.3,0.1

Type RM Length L Ch R = 1,10747,484,484,484
BEGIN DESCRIPTION:
268
END DESCRIPTION:
XS GIS Cut Line= 3
      1526405.02      6785587.99      1526305.68      6785637.06
      1526205.00      6785588.00
#Sta/Elev= 30
  4889.2 2219.88  4892.0 2219.88  4897.7 2217.23  4903.2 2216.63  4911.5 2213.38
  4920.1 2207.10  4925.7 2209.03  4933.8 2208.54  4942.5 2205.88  4948.1 2206.22
  4965.0 2195.95  4970.6 2200.29  4978.4 2195.64  4985.4 2194.77  4985.7 2194.27
  4989.4 2194.77  4993.0 2194.84  4997.6 2198.00  5007.8 2199.19  5013.4 2199.09
  5023.0 2201.09  5030.3 2204.99  5035.9 2204.03  5052.9 2207.79  5058.4 2207.33
  5081.0 2210.27  5097.9 2217.39  5103.5 2216.36  5109.2 2218.28  5112.0 2218.28
#Mann=3,-1,0
  4889.2    0.16       0  4985.4    0.07       0  4989.4    0.16       0
Bank Sta=4985.4,4989.4
Exp/Cntr=0.3,0.1

Type RM Length L Ch R = 1,10263,496,496,496
BEGIN DESCRIPTION:
267
END DESCRIPTION:
XS GIS Cut Line= 3
      1526455.03      6785188.00      1526310.75      6785185.66
      1526051.68      6785239.52
#Sta/Elev= 30
  4855.7 2216.34  4865.7 2214.79  4875.7 2211.81  4905.7 2199.14  4915.7 2196.68
  4945.7 2195.12  4955.7 2193.39  4975.7 2188.00  4983.7 2187.10  4984.0 2186.60
  4987.5 2186.60  4987.7 2187.10  5005.9 2187.10  5016.1 2187.93  5026.3 2191.43
  5033.7 2196.19  5038.8 2194.17  5046.7 2198.93  5067.2 2202.64  5083.8 2204.80
  5088.9 2206.46  5097.8 2206.91  5104.8 2206.16  5118.2 2205.62  5133.9 2206.18
  5178.9 2209.60  5220.4 2214.52  5234.1 2217.86  5240.8 2220.32  5264.6 2221.95
#Mann=4,-1,0
  4855.7    0.16       0  4983.7    0.07       0  4987.7    0.16       0
  5104.8    0.07       0
Bank Sta=4983.7,4987.7
Exp/Cntr=0.3,0.1

Type RM Length L Ch R = 1,9767,315,315,315
BEGIN DESCRIPTION:
266
END DESCRIPTION:
XS GIS Cut Line= 3
      1526504.98      6784887.99      1526357.38      6784793.97
      1526071.41      6784887.89
#Sta/Elev= 30
  4825.0 2213.11  4842.0 2211.67  4847.8 2211.23  4884.2 2200.94  4905.4 2190.83
  4955.4 2187.09  4978.2 2183.36  4984.1 2183.75  4991.0 2180.85  5003.9 2179.77
  5013.0 2177.05  5021.6 2176.07  5021.8 2175.57  5025.6 2176.07  5028.9 2182.20
  5034.1 2179.80  5060.7 2189.71  5066.0 2189.21  5100.6 2194.61  5124.3 2198.76
  5139.3 2199.79  5161.4 2205.57  5187.9 2209.80  5213.0 2210.96  5225.0 2210.22
  5251.6 2204.72  5256.8 2206.03  5265.6 2205.56  5283.4 2207.37  5301.0 2210.34
#Mann=5,-1,0
  4825.0    0.07       0  4842.0    0.16       0  5021.6    0.07       0
  5025.6    0.16       0  5100.6    0.07       0
Bank Sta=5021.6,5025.6
Exp/Cntr=0.3,0.1

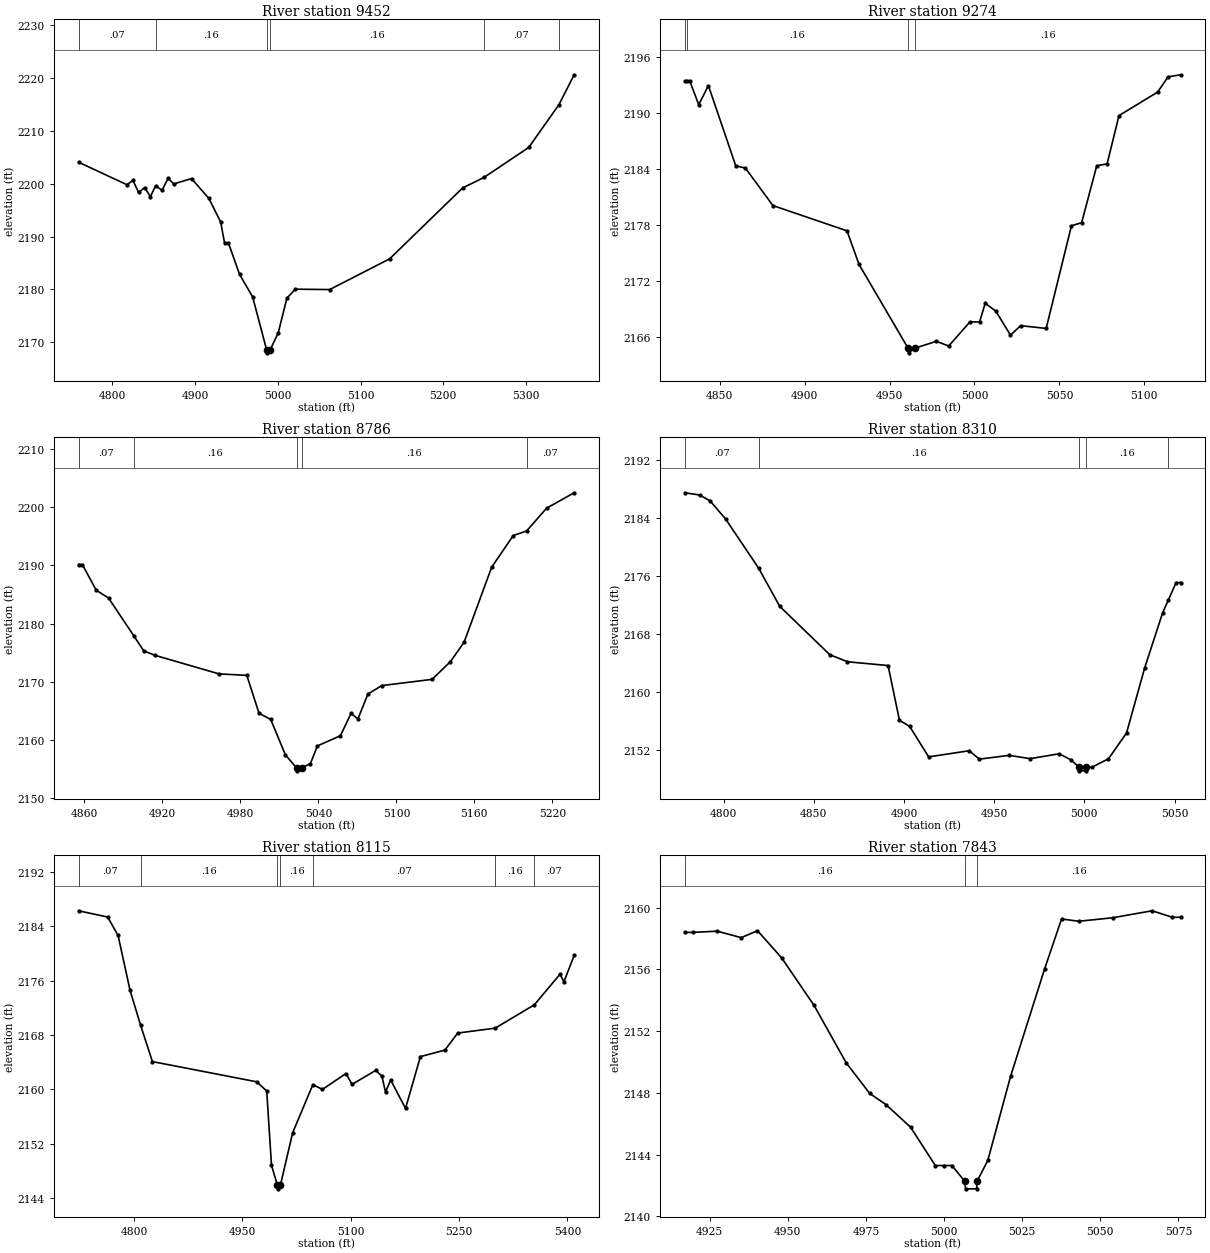
Type RM Length L Ch R = 1,9452,178,178,178
BEGIN DESCRIPTION:
869
END DESCRIPTION:
XS GIS Cut Line= 3
      1526544.62      6784651.25      1526413.20      6784526.40
      1526009.54      6784418.10
#Sta/Elev= 30
  4759.0 2204.10  4817.5 2199.83  4824.8 2200.64  4831.7 2198.36  4839.0 2199.30
  4845.9 2197.57  4852.2 2199.64  4860.0 2198.77  4867.3 2201.06  4874.2 2199.98
  4895.6 2200.99  4916.6 2197.23  4930.8 2192.79  4935.6 2188.77  4940.3 2188.77
  4953.7 2182.84  4969.5 2178.59  4986.5 2168.49  4986.7 2167.99  4990.5 2168.49
  5000.5 2171.81  5010.9 2178.35  5021.2 2180.05  5062.6 2179.97  5135.1 2185.79
  5223.3 2199.21  5249.1 2201.20  5303.3 2206.89  5339.7 2214.97  5358.2 2220.65
#Mann=6,-1,0
  4759.0    0.07       0  4852.2    0.16       0  4986.5    0.07       0
  4990.5    0.16       0  5249.1    0.07       0  5339.7    0.16       0
Bank Sta=4986.5,4990.5
Exp/Cntr=0.3,0.1

Type RM Length L Ch R = 1,9274,488,488,488
BEGIN DESCRIPTION:
265
END DESCRIPTION:
XS GIS Cut Line= 3
      1526555.01      6784538.02      1526473.43      6784388.31
      1526405.02      6784288.02
#Sta/Elev= 30
  4829.5 2193.40  4830.5 2193.40  4832.4 2193.40  4837.6 2190.90  4843.3 2192.95
  4859.4 2184.34  4865.1 2184.09  4881.3 2180.07  4924.9 2177.36  4932.0 2173.75
  4960.9 2164.76  4961.2 2164.26  4964.9 2164.76  4977.6 2165.50  4984.8 2164.99
  4997.3 2167.58  5003.0 2167.58  5006.3 2169.58  5012.5 2168.75  5021.2 2166.16
  5027.2 2167.18  5042.2 2166.88  5057.1 2177.90  5063.1 2178.23  5072.0 2184.34
  5078.1 2184.55  5085.1 2189.73  5107.9 2192.26  5114.0 2193.89  5121.4 2194.11
#Mann=4,-1,0
  4829.5    0.07       0  4830.5    0.16       0  4960.9    0.07       0
  4964.9    0.16       0
Bank Sta=4960.9,4964.9
Exp/Cntr=0.3,0.1

Type RM Length L Ch R = 1,8786,476,476,476
BEGIN DESCRIPTION:
264
END DESCRIPTION:
XS GIS Cut Line= 3
      1526855.03      6784138.02      1526732.13      6784061.83
      1526654.98      6783837.95
#Sta/Elev= 30
  4855.4 2190.15  4858.4 2190.15  4869.0 2185.75  4878.5 2184.41  4898.2 2177.83
  4905.6 2175.33  4914.3 2174.56  4963.5 2171.38  4984.9 2171.13  4994.3 2164.62
  5003.3 2163.55  5014.6 2157.47  5023.2 2155.23  5023.5 2154.73  5027.2 2155.23
  5033.9 2155.99  5039.2 2159.00  5056.9 2160.76  5065.1 2164.58  5070.4 2163.65
  5078.1 2167.91  5088.7 2169.37  5127.5 2170.44  5141.6 2173.49  5152.1 2176.82
  5173.3 2189.69  5189.9 2195.13  5200.2 2195.92  5215.6 2199.84  5236.8 2202.48
#Mann=5,-1,0
  4855.4    0.07       0  4898.2    0.16       0  5023.2    0.07       0
  5027.2    0.16       0  5200.2    0.07       0
Bank Sta=5023.2,5027.2
Exp/Cntr=0.3,0.1

Type RM Length L Ch R = 1,8310,195,195,195
BEGIN DESCRIPTION:
263
END DESCRIPTION:
XS GIS Cut Line= 3
      1527104.99      6783788.00      1526908.36      6783686.24
      1526854.99      6783688.00
#Sta/Elev= 30
  4778.6 2187.44  4786.8 2187.13  4792.5 2186.33  4801.1 2183.84  4819.5 2177.03
  4831.1 2171.81  4858.9 2165.14  4868.7 2164.17  4891.2 2163.65  4897.5 2156.12
  4903.2 2155.26  4913.7 2151.07  4936.2 2151.92  4941.8 2150.76  4958.3 2151.28
  4970.0 2150.83  4986.1 2151.50  4992.5 2150.67  4997.1 2149.65  4997.3 2149.15
  5000.8 2149.15  5001.1 2149.65  5004.2 2149.65  5013.4 2150.81  5023.4 2154.36
  5033.4 2163.27  5043.4 2170.90  5046.6 2172.68  5050.9 2175.08  5053.4 2175.08
#Mann=5,-1,0
  4778.6    0.07       0  4819.5    0.16       0  4997.1    0.07       0
  5001.1    0.16       0  5046.6    0.07       0
Bank Sta=4997.1,5001.1
Exp/Cntr=0.3,0.1

Type RM Length L Ch R = 1,8115,272,272,272
BEGIN DESCRIPTION:
868
END DESCRIPTION:
XS GIS Cut Line= 2
      1527274.17      6783616.12      1526608.55      6783448.89
#Sta/Elev= 30
  4723.1 2186.26  4763.5 2185.34  4777.9 2182.63  4794.4 2174.59  4809.1 2169.43
  4825.4 2164.10  4969.7 2161.13  4983.7 2159.78  4990.3 2148.87  4998.6 2145.90
  4998.9 2145.40  5002.6 2145.90  5019.6 2153.64  5047.6 2160.71  5060.8 2160.01
  5093.4 2162.34  5101.9 2160.75  5134.7 2162.81  5143.1 2161.97  5148.2 2159.63
  5155.3 2161.39  5175.9 2157.22  5196.5 2164.83  5230.5 2165.79  5248.1 2168.29
  5300.0 2169.01  5354.2 2172.44  5389.9 2176.95  5395.1 2175.80  5409.4 2179.69
#Mann=7,-1,0
  4723.1    0.07       0  4809.1    0.16       0  4998.6    0.07       0
  5002.6    0.16       0  5047.6    0.07       0  5300.0    0.16       0
  5354.2    0.07       0
Bank Sta=4998.6,5002.6
Exp/Cntr=0.3,0.1

Type RM Length L Ch R = 1,7843,187,187,187
BEGIN DESCRIPTION:
262
END DESCRIPTION:
XS GIS Cut Line= 3
      1527105.00      6783388.01      1527084.80      6783307.61
      1527055.01      6783238.02
#Sta/Elev= 27
  4917.1 2158.39  4919.7 2158.39  4927.4 2158.47  4935.1 2158.05  4940.3 2158.50
  4948.0 2156.75  4958.4 2153.66  4968.7 2149.94  4976.2 2147.96  4981.4 2147.24
  4989.3 2145.77  4997.2 2143.29  5000.0 2143.29  5002.5 2143.29  5006.6 2142.28
  5006.9 2141.78  5010.4 2141.78  5010.6 2142.28  5014.0 2143.62  5021.3 2149.08
  5032.2 2156.04  5037.6 2159.26  5043.1 2159.11  5054.0 2159.34  5066.6 2159.79
  5073.0 2159.37  5075.7 2159.37
#Mann=3,-1,0
  4917.1    0.16       0  5006.6    0.07       0  5010.6    0.16       0
Bank Sta=5006.6,5010.6
Exp/Cntr=0.3,0.1

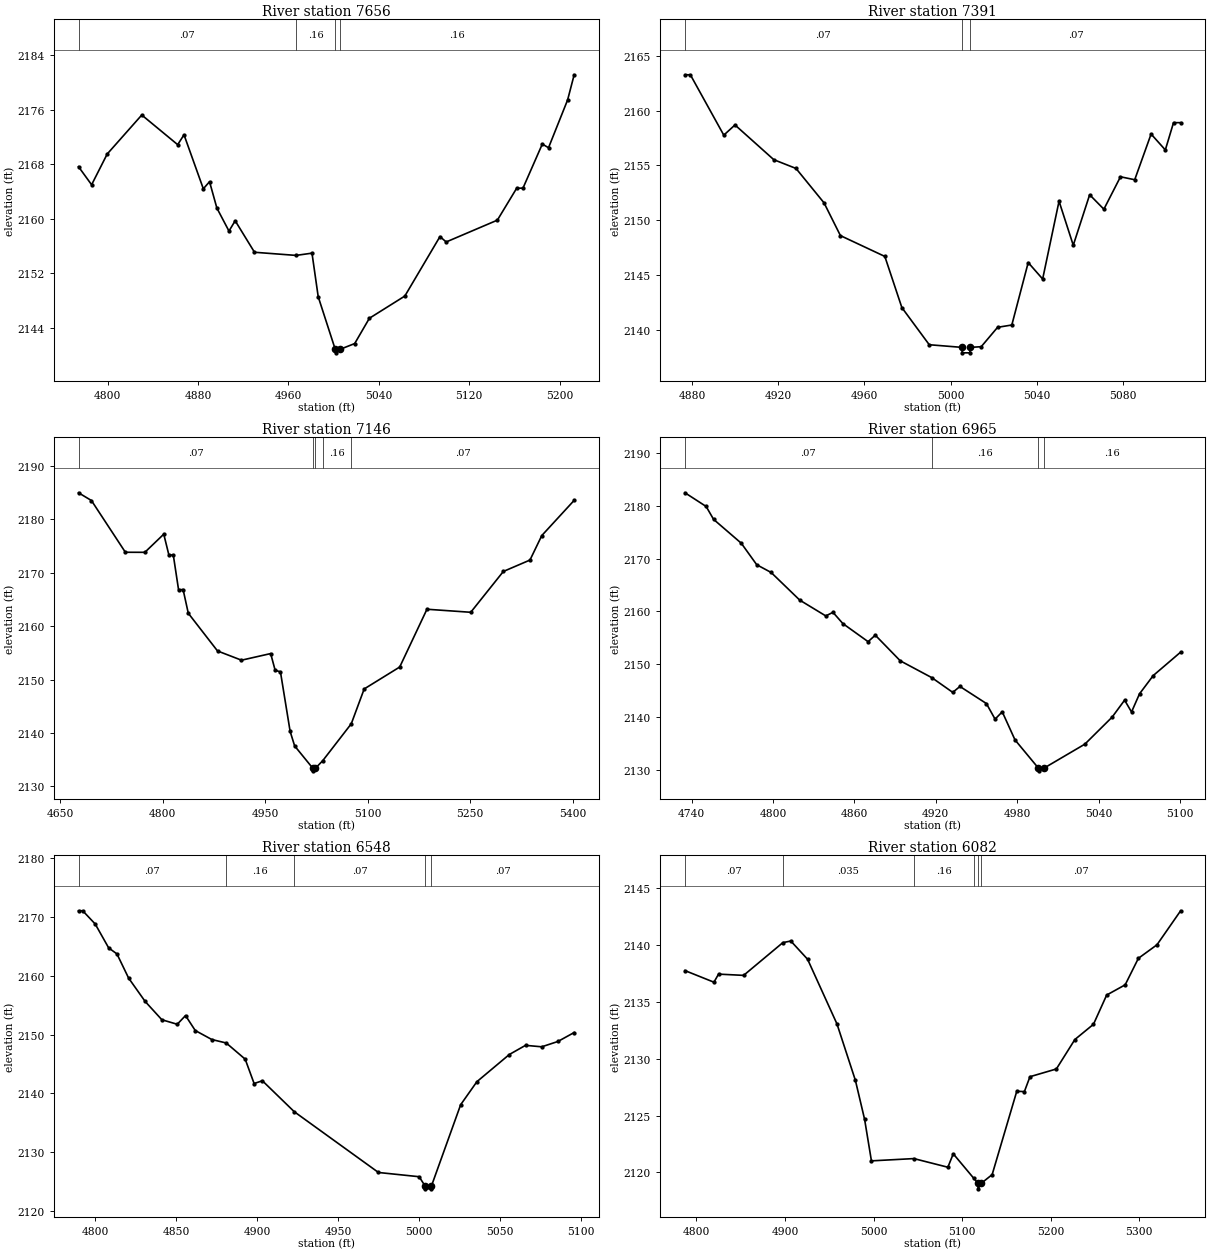
Type RM Length L Ch R = 1,7656,265,265,265
BEGIN DESCRIPTION:
867
END DESCRIPTION:
XS GIS Cut Line= 2
      1527349.75      6783448.49      1527160.08      6783052.80
#Sta/Elev= 30
  4774.1 2167.63  4785.7 2164.98  4799.5 2169.49  4830.1 2175.21  4861.9 2170.86
  4867.5 2172.31  4884.6 2164.39  4890.1 2165.43  4896.6 2161.56  4907.3 2158.19
  4912.8 2159.70  4929.9 2155.08  4966.7 2154.62  4980.8 2154.95  4986.3 2148.56
  5001.4 2140.83  5001.7 2140.33  5005.4 2140.83  5018.6 2141.69  5031.6 2145.40
  5063.0 2148.66  5094.1 2157.38  5099.6 2156.59  5144.9 2159.79  5162.0 2164.47
  5167.6 2164.49  5184.7 2170.95  5190.2 2170.41  5207.1 2177.42  5212.9 2181.11
#Mann=4,-1,0
  4774.1    0.07       0  4966.7    0.16       0  5001.4    0.07       0
  5005.4    0.16       0
Bank Sta=5001.4,5005.4
Exp/Cntr=0.3,0.1

Type RM Length L Ch R = 1,7391,245,245,245
BEGIN DESCRIPTION:
261
END DESCRIPTION:
XS GIS Cut Line= 3
      1527604.96      6783187.99      1527485.41      6783158.21
      1527405.04      6783088.03
#Sta/Elev= 30
  4876.8 2163.28  4879.3 2163.28  4894.8 2157.77  4900.0 2158.70  4918.0 2155.53
  4928.3 2154.73  4941.3 2151.59  4948.9 2148.60  4969.5 2146.70  4977.4 2142.03
  4990.1 2138.64  5005.2 2138.40  5005.4 2137.90  5008.9 2137.90  5009.2 2138.40
  5014.2 2138.46  5021.8 2140.23  5028.4 2140.44  5036.0 2146.14  5042.7 2144.64
  5050.3 2151.74  5056.9 2147.72  5064.5 2152.33  5071.1 2151.01  5078.8 2153.97
  5085.4 2153.70  5093.0 2157.87  5099.6 2156.42  5103.4 2158.91  5106.7 2158.91
#Mann=3,-1,0
  4876.8    0.07       0  5005.2    0.07       0  5009.2    0.07       0
Bank Sta=5005.2,5009.2
Exp/Cntr=0.3,0.1

Type RM Length L Ch R = 1,7146,181,181,181
BEGIN DESCRIPTION:
866
END DESCRIPTION:
XS GIS Cut Line= 3
      1527767.09      6783182.31      1527510.79      6782886.58
      1527189.39      6782794.75
#Sta/Elev= 30
  4676.7 2185.00  4695.6 2183.55  4745.3 2173.85  4773.8 2173.84  4801.5 2177.24
  4808.9 2173.39  4815.5 2173.30  4823.2 2166.80  4829.8 2166.87  4837.4 2162.42
  4880.2 2155.35  4915.3 2153.62  4958.0 2154.86  4964.6 2151.71  4972.3 2151.45
  4986.5 2140.27  4993.1 2137.55  5019.6 2133.38  5019.9 2132.88  5023.6 2133.38
  5034.2 2134.78  5076.0 2141.70  5094.9 2148.23  5146.9 2152.34  5186.8 2163.17
  5250.9 2162.60  5298.6 2170.25  5337.6 2172.39  5354.9 2176.98  5402.3 2183.58
#Mann=5,-1,0
  4676.7    0.07       0  5019.6    0.07       0  5023.6    0.07       0
  5034.2    0.16       0  5076.0    0.07       0
Bank Sta=5019.6,5023.6
Exp/Cntr=0.3,0.1

Type RM Length L Ch R = 1,6965,417,417,417
BEGIN DESCRIPTION:
260
END DESCRIPTION:
XS GIS Cut Line= 3
      1527804.99      6783137.98      1527718.51      6782887.59
      1527705.00      6782788.01
#Sta/Elev= 30
  4735.1 2182.45  4750.7 2179.86  4756.2 2177.42  4776.6 2172.91  4788.0 2168.84
  4798.6 2167.38  4819.7 2162.15  4838.9 2159.16  4844.2 2159.84  4851.5 2157.71
  4870.1 2154.29  4875.4 2155.52  4893.8 2150.67  4917.1 2147.48  4932.5 2144.70
  4937.8 2145.82  4957.3 2142.59  4963.7 2139.64  4969.0 2141.02  4978.4 2135.71
  4995.7 2130.36  4996.0 2129.86  4999.7 2130.36  5029.9 2134.91  5050.0 2140.02
  5059.2 2143.23  5064.3 2140.99  5070.2 2144.43  5080.3 2147.88  5100.5 2152.31
#Mann=4,-1,0
  4735.1    0.07       0  4917.1    0.16       0  4995.7    0.07       0
  4999.7    0.16       0
Bank Sta=4995.7,4999.7
Exp/Cntr=0.3,0.1

Type RM Length L Ch R = 1,6548,466,466,466
BEGIN DESCRIPTION:
259
END DESCRIPTION:
XS GIS Cut Line= 3
      1528105.02      6782738.01      1527900.57      6782689.64
      1527804.98      6782688.00
#Sta/Elev= 30
  4789.9 2171.04  4792.5 2171.04  4800.2 2168.79  4808.5 2164.73  4813.6 2163.71
  4820.8 2159.60  4831.0 2155.63  4841.3 2152.52  4850.8 2151.75  4855.9 2153.23
  4861.9 2150.69  4872.1 2149.16  4881.0 2148.57  4892.7 2145.82  4898.2 2141.68
  4903.3 2142.15  4923.0 2136.88  4974.9 2126.56  5000.0 2125.84  5003.6 2124.28
  5003.8 2123.78  5007.3 2123.78  5007.6 2124.28  5025.6 2138.08  5035.6 2141.99
  5055.6 2146.61  5065.6 2148.17  5075.6 2147.92  5085.6 2148.83  5095.6 2150.35
#Mann=5,-1,0
  4789.9    0.07       0  4881.0    0.16       0  4923.0    0.07       0
  5003.6    0.07       0  5007.6    0.07       0
Bank Sta=5003.6,5007.6
Exp/Cntr=0.3,0.1

Type RM Length L Ch R = 1,6082,452,452,452
BEGIN DESCRIPTION:
258
END DESCRIPTION:
XS GIS Cut Line= 3
      1528139.62      6782592.76      1528080.09      6782388.25
      1527883.76      6782102.62
#Sta/Elev= 30
  4787.0 2137.75  4819.7 2136.73  4824.9 2137.44  4853.2 2137.33  4897.5 2140.21
  4906.5 2140.35  4925.4 2138.75  4958.6 2133.06  4979.4 2128.10  4989.8 2124.67
  4997.5 2121.02  5045.4 2121.22  5083.8 2120.46  5089.9 2121.64  5112.9 2119.50
  5117.7 2119.06  5117.9 2118.56  5121.7 2119.06  5133.8 2119.81  5161.6 2127.14
  5170.2 2127.11  5176.5 2128.42  5206.3 2129.10  5227.2 2131.69  5248.2 2133.03
  5263.1 2135.60  5284.0 2136.50  5298.9 2138.83  5319.9 2140.02  5346.6 2143.01
#Mann=6,-1,0
  4787.0    0.07       0  4897.5   0.035       0  5045.4    0.16       0
  5112.9    0.07       0  5117.7   0.035       0  5121.7    0.07       0
Bank Sta=5117.7,5121.7
Exp/Cntr=0.3,0.1

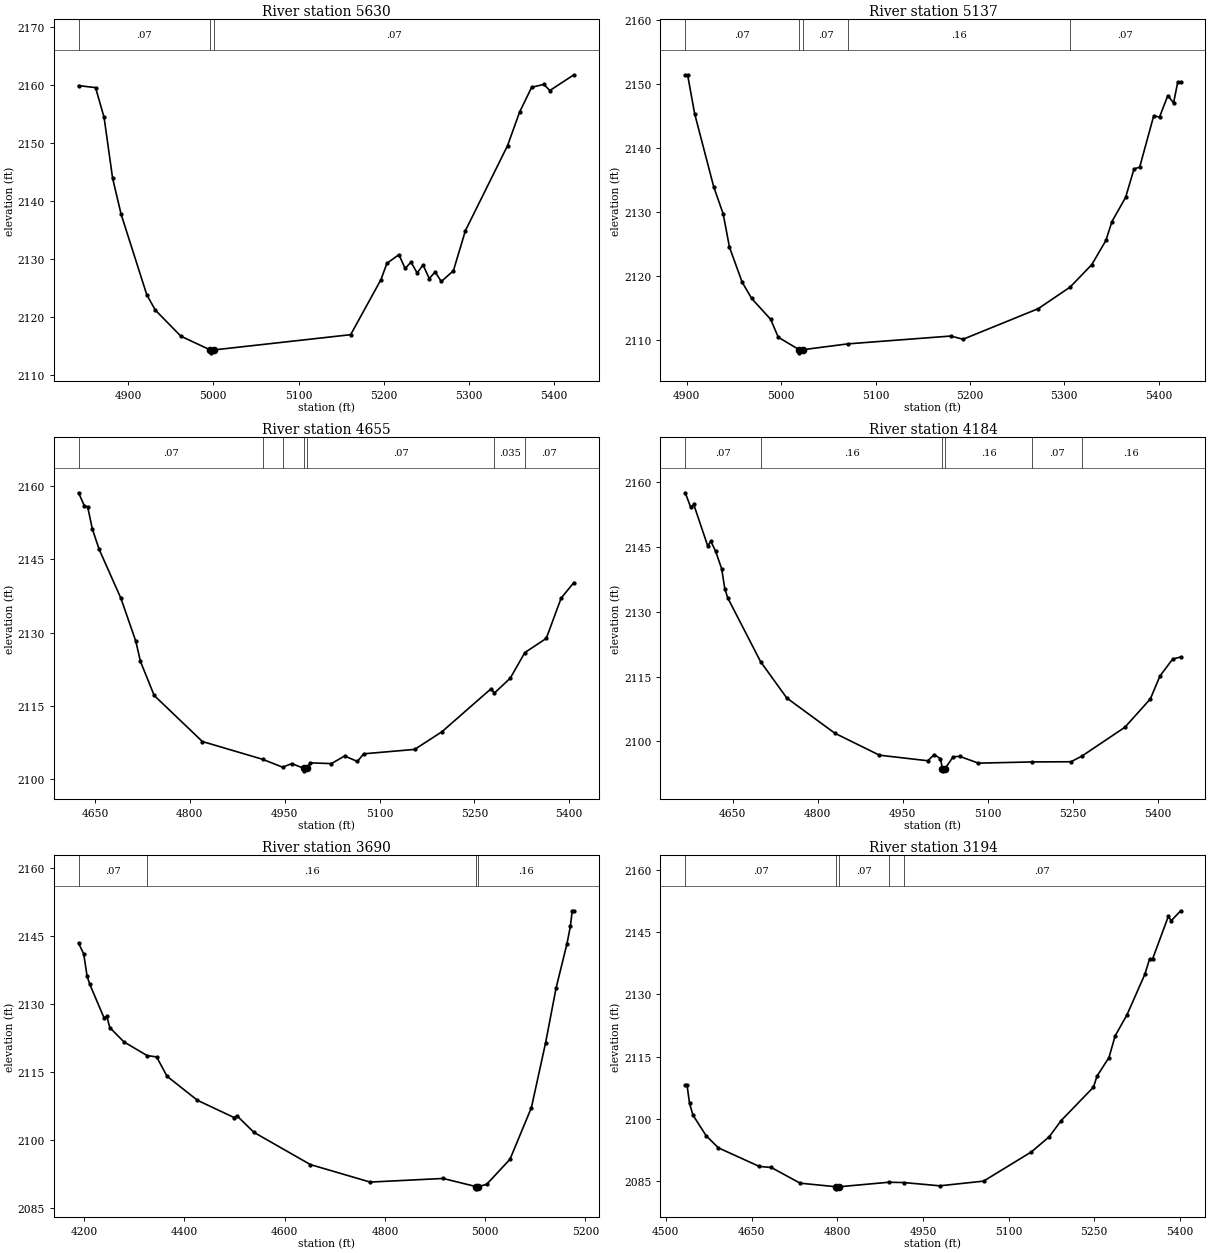
Type RM Length L Ch R = 1,5630,493,493,493
BEGIN DESCRIPTION:
257
END DESCRIPTION:
XS GIS Cut Line= 3
      1528455.00      6782537.99      1528461.07      6782379.91
      1528154.97      6782087.97
#Sta/Elev= 30
  4841.8 2159.85  4861.8 2159.51  4871.8 2154.38  4881.8 2143.90  4891.8 2137.68
  4921.9 2123.80  4931.9 2121.16  4961.9 2116.66  4996.4 2114.29  4996.7 2113.79
  5000.5 2114.29  5161.1 2116.92  5196.7 2126.43  5203.6 2129.22  5217.7 2130.71
  5225.0 2128.33  5231.9 2129.43  5239.1 2127.55  5246.0 2128.95  5253.3 2126.59
  5260.2 2127.73  5267.4 2126.09  5281.6 2127.93  5295.7 2134.85  5345.1 2149.49
  5359.3 2155.30  5373.4 2159.56  5387.6 2160.06  5394.8 2159.01  5423.0 2161.72
#Mann=3,-1,0
  4841.8    0.07       0  4996.4    0.07       0  5000.5    0.07       0
Bank Sta=4996.4,5000.5
Exp/Cntr=0.3,0.1

Type RM Length L Ch R = 1,5137,482,482,482
BEGIN DESCRIPTION:
256
END DESCRIPTION:
XS GIS Cut Line= 3
      1528905.00      6782288.00      1528894.52      6782186.84
      1528654.97      6781837.96
#Sta/Elev= 30
  4898.3 2151.44  4900.8 2151.44  4908.3 2145.35  4928.5 2133.95  4938.5 2129.74
  4945.2 2124.53  4958.6 2119.08  4968.7 2116.54  4988.8 2113.29  4996.9 2110.49
  5018.9 2108.56  5019.3 2108.06  5023.5 2108.56  5070.6 2109.46  5179.6 2110.68
  5192.7 2110.18  5272.3 2114.95  5306.2 2118.33  5329.1 2121.83  5344.0 2125.59
  5350.4 2128.54  5364.9 2132.32  5373.8 2136.75  5379.8 2137.04  5394.7 2145.05
  5400.8 2144.84  5409.6 2148.19  5415.7 2147.05  5420.1 2150.27  5423.2 2150.27
#Mann=5,-1,0
  4898.3    0.07       0  5018.9    0.07       0  5023.5    0.07       0
  5070.6    0.16       0  5306.2    0.07       0
Bank Sta=5018.9,5023.5
Exp/Cntr=0.3,0.1

Type RM Length L Ch R = 1,4655,471,471,471
BEGIN DESCRIPTION:
255
END DESCRIPTION:
XS GIS Cut Line= 3
      1529455.01      6781938.00      1529109.41      6781789.63
      1528704.99      6781838.00
#Sta/Elev= 30
  4623.9 2158.58  4633.0 2155.98  4638.4 2155.70  4645.7 2151.23  4656.5 2147.03
  4691.0 2137.00  4714.5 2128.24  4721.9 2124.10  4743.6 2117.15  4819.8 2107.74
  4915.0 2104.11  4946.8 2102.49  4961.0 2103.23  4980.7 2102.25  4981.0 2101.75
  4985.3 2102.25  4990.0 2103.38  5023.9 2103.23  5044.7 2104.79  5064.9 2103.67
  5074.9 2105.23  5155.5 2106.13  5198.8 2109.76  5276.2 2118.52  5281.6 2117.65
  5306.6 2120.68  5329.7 2125.92  5363.6 2128.82  5387.1 2137.05  5407.3 2140.24
#Mann=7,-1,0
  4623.9    0.07       0  4915.0    0.16       0  4946.8    0.07       0
  4980.7    0.07       0  4985.3    0.07       0  5281.6   0.035       0
  5329.7    0.07       0
Bank Sta=4980.7,4985.3
Exp/Cntr=0.3,0.1

Type RM Length L Ch R = 1,4184,494,494,494
BEGIN DESCRIPTION:
254
END DESCRIPTION:
XS GIS Cut Line= 3
      1529505.00      6781888.01      1529349.89      6781482.89
      1529154.98      6781087.97
#Sta/Elev= 30
  4566.2 2157.50  4575.9 2154.13  4581.2 2154.80  4605.9 2145.20  4611.3 2146.29
  4619.7 2144.01  4630.5 2139.91  4636.0 2135.33  4641.3 2133.16  4699.3 2118.40
  4745.4 2110.03  4830.2 2101.88  4908.9 2096.80  4994.4 2095.51  5005.5 2096.95
  5016.6 2095.97  5020.0 2093.68  5020.3 2093.18  5024.6 2093.68  5038.9 2096.41
  5050.3 2096.54  5083.5 2094.96  5178.2 2095.24  5246.8 2095.28  5266.3 2096.60
  5342.1 2103.27  5387.0 2109.83  5403.9 2115.12  5426.3 2119.03  5440.4 2119.52
#Mann=6,-1,0
  4566.2    0.07       0  4699.3    0.16       0  5020.0    0.07       0
  5024.6    0.16       0  5178.2    0.07       0  5266.3    0.16       0
Bank Sta=5020,5024.6
Exp/Cntr=0.3,0.1

Type RM Length L Ch R = 1,3690,496,496,496
BEGIN DESCRIPTION:
253
END DESCRIPTION:
XS GIS Cut Line= 3
      1529755.01      6781838.05      1529535.88      6781057.01
      1529405.00      6780938.00
#Sta/Elev= 30
  4188.8 2143.50  4199.2 2141.09  4205.9 2136.22  4211.1 2134.44  4240.0 2126.92
  4245.2 2127.36  4251.2 2124.85  4279.3 2121.70  4325.7 2118.67  4344.6 2118.38
  4365.4 2114.11  4426.0 2108.81  4499.4 2104.99  4504.6 2105.42  4538.7 2101.74
  4651.3 2094.63  4770.5 2090.77  4915.9 2091.57  4981.6 2089.78  4982.0 2089.28
  4986.5 2089.78  5003.0 2090.28  5049.5 2095.82  5092.1 2107.19  5120.5 2121.53
  5141.4 2133.60  5163.0 2143.32  5169.8 2147.15  5173.5 2150.61  5176.9 2150.61
#Mann=4,-1,0
  4188.8    0.07       0  4325.7    0.16       0  4981.6    0.07       0
  4986.5    0.16       0
Bank Sta=4981.6,4986.5
Exp/Cntr=0.3,0.1

Type RM Length L Ch R = 1,3194,419,419,419
BEGIN DESCRIPTION:
252
END DESCRIPTION:
XS GIS Cut Line= 3
      1530205.02      6781188.03      1529938.70      6780805.50
      1529554.99      6780688.00
#Sta/Elev= 30
  4533.9 2108.18  4537.0 2108.18  4541.4 2103.75  4547.4 2100.86  4570.5 2095.87
  4592.0 2092.94  4663.5 2088.46  4684.5 2088.20  4735.1 2084.41  4798.1 2083.54
  4798.5 2083.04  4803.0 2083.54  4890.2 2084.63  4916.7 2084.56  4979.5 2083.77
  5056.2 2084.90  5139.8 2091.95  5171.2 2095.62  5192.1 2099.54  5248.6 2107.60
  5254.9 2110.28  5275.8 2114.76  5286.6 2120.00  5307.2 2125.05  5338.5 2134.84
  5346.9 2138.56  5352.1 2138.56  5379.7 2148.87  5384.9 2147.83  5401.3 2150.23
#Mann=5,-1,0
  4533.9    0.07       0  4798.1    0.07       0  4803.0    0.07       0
  4890.2    0.16       0  4916.7    0.07       0
Bank Sta=4798.1,4803
Exp/Cntr=0.3,0.1

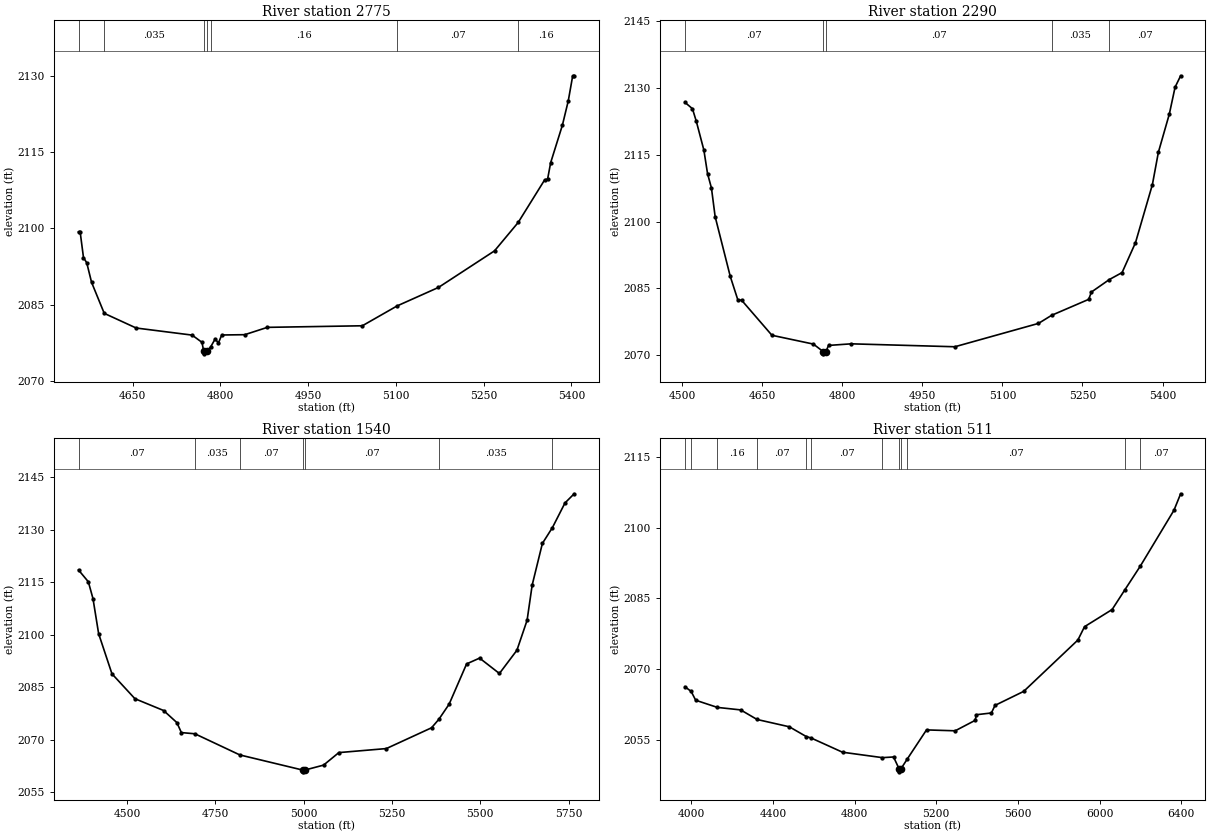
Type RM Length L Ch R = 1,2775,485,485,485
BEGIN DESCRIPTION:
251
END DESCRIPTION:
XS GIS Cut Line= 3
      1530455.02      6780988.04      1530260.52      6780590.35
      1530305.00      6780188.00
#Sta/Elev= 30
  4557.3 2099.30  4560.1 2099.30  4565.8 2094.27  4571.4 2093.23  4579.6 2089.41
  4601.3 2083.31  4655.9 2080.43  4751.5 2079.04  4768.4 2077.62  4771.4 2075.86
  4771.8 2075.36  4776.5 2075.86  4783.3 2076.73  4790.9 2078.27  4796.5 2077.49
  4802.2 2079.06  4841.5 2079.12  4880.2 2080.56  5042.6 2080.87  5102.1 2084.77
  5172.8 2088.40  5268.6 2095.58  5309.1 2101.16  5354.4 2109.53  5359.4 2109.68
  5364.6 2112.89  5384.7 2120.27  5394.7 2125.02  5402.3 2129.96  5404.8 2129.96
#Mann=7,-1,0
  4557.3    0.07       0  4601.3   0.035       0  4771.4    0.07       0
  4776.5   0.035       0  4783.3    0.16       0  5102.1    0.07       0
  5309.1    0.16       0
Bank Sta=4771.4,4776.5
Exp/Cntr=0.3,0.1

Type RM Length L Ch R = 1,2290,750,750,750
BEGIN DESCRIPTION:
250
END DESCRIPTION:
XS GIS Cut Line= 3
      1531055.03      6780888.03      1530695.15      6780548.60
      1530554.99      6780137.96
#Sta/Elev= 30
  4505.3 2126.80  4519.3 2125.38  4526.6 2122.52  4540.7 2116.08  4547.6 2110.78
  4554.9 2107.55  4561.8 2101.14  4590.1 2087.72  4604.3 2082.43  4611.5 2082.34
  4668.2 2074.47  4745.9 2072.49  4764.3 2070.80  4764.7 2070.30  4769.5 2070.80
  4774.2 2072.19  4816.7 2072.55  5010.9 2071.89  5167.6 2077.14  5192.1 2078.95
  5261.6 2082.54  5266.8 2084.19  5300.4 2087.00  5324.2 2088.56  5349.3 2095.27
  5381.0 2108.33  5392.2 2115.59  5412.7 2124.17  5423.5 2130.22  5433.9 2132.78
#Mann=5,-1,0
  4505.3    0.07       0  4764.3    0.07       0  4769.5    0.07       0
  5192.1   0.035       0  5300.4    0.07       0
Bank Sta=4764.3,4769.5
Exp/Cntr=0.3,0.1

Type RM Length L Ch R = 1,1540,1029,1029,1029
BEGIN DESCRIPTION:
805
END DESCRIPTION:
XS GIS Cut Line= 3
      1531538.06      6780622.28      1531229.89      6780071.04
      1530626.58      6779589.26
#Sta/Elev= 30
  4362.3 2118.49  4390.1 2115.12  4403.3 2110.30  4419.3 2100.27  4457.0 2088.81
  4522.1 2081.69  4603.2 2078.32  4640.8 2074.87  4653.6 2072.01  4691.8 2071.67
  4819.2 2065.62  4997.5 2061.29  4997.9 2060.79  5002.9 2061.29  5056.2 2062.71
  5099.5 2066.29  5234.0 2067.44  5362.0 2073.38  5382.6 2075.79  5411.7 2080.11
  5461.3 2091.64  5498.1 2093.30  5554.2 2088.90  5603.8 2095.55  5632.6 2104.11
  5647.0 2114.18  5675.9 2126.08  5704.4 2130.62  5739.9 2137.65  5765.9 2140.27
#Mann=7,-1,0
  4362.3    0.07       0  4691.8   0.035       0  4819.2    0.07       0
  4997.5    0.07       0  5002.9    0.07       0  5382.6   0.035       0
  5704.4    0.07       0
Bank Sta=4997.5,5002.9
Exp/Cntr=0.3,0.1

Type RM Length L Ch R = 1,511,0,0,0
BEGIN DESCRIPTION:
249
END DESCRIPTION:
XS GIS Cut Line= 4
      1531429.55      6780179.52      1531581.45      6779801.94
      1531613.63      6779178.76      1530280.03      6778763.01
#Sta/Elev= 30
  3969.0 2066.26  3999.2 2065.27  4021.5 2063.40  4127.7 2061.88  4241.8 2061.35
  4322.1 2059.32  4480.1 2057.77  4563.6 2055.69  4586.1 2055.41  4740.6 2052.38
  4936.0 2051.23  4990.7 2051.37  5019.3 2048.72  5019.7 2048.22  5024.8 2048.72
  5058.8 2051.00  5152.1 2057.11  5292.6 2056.92  5390.2 2059.13  5396.6 2060.33
  5469.9 2060.70  5487.7 2062.31  5628.2 2065.28  5893.5 2076.16  5926.1 2078.99
  6061.3 2082.63  6123.7 2086.81  6199.3 2091.83  6364.4 2103.69  6396.9 2107.17
#Mann=12,-1,0
  3969.0    0.16       0  3999.2    0.07       0  4127.7    0.16       0
  4322.1    0.07       0  4563.6   0.035       0  4586.1    0.07       0
  4936.0    0.16       0  5019.3    0.07       0  5024.8    0.16       0
  5058.8    0.07       0  6123.7   0.035       0  6199.3    0.07       0
Bank Sta=5019.3,5024.8
Exp/Cntr=0.3,0.1

Chan Stop Cuts=-1