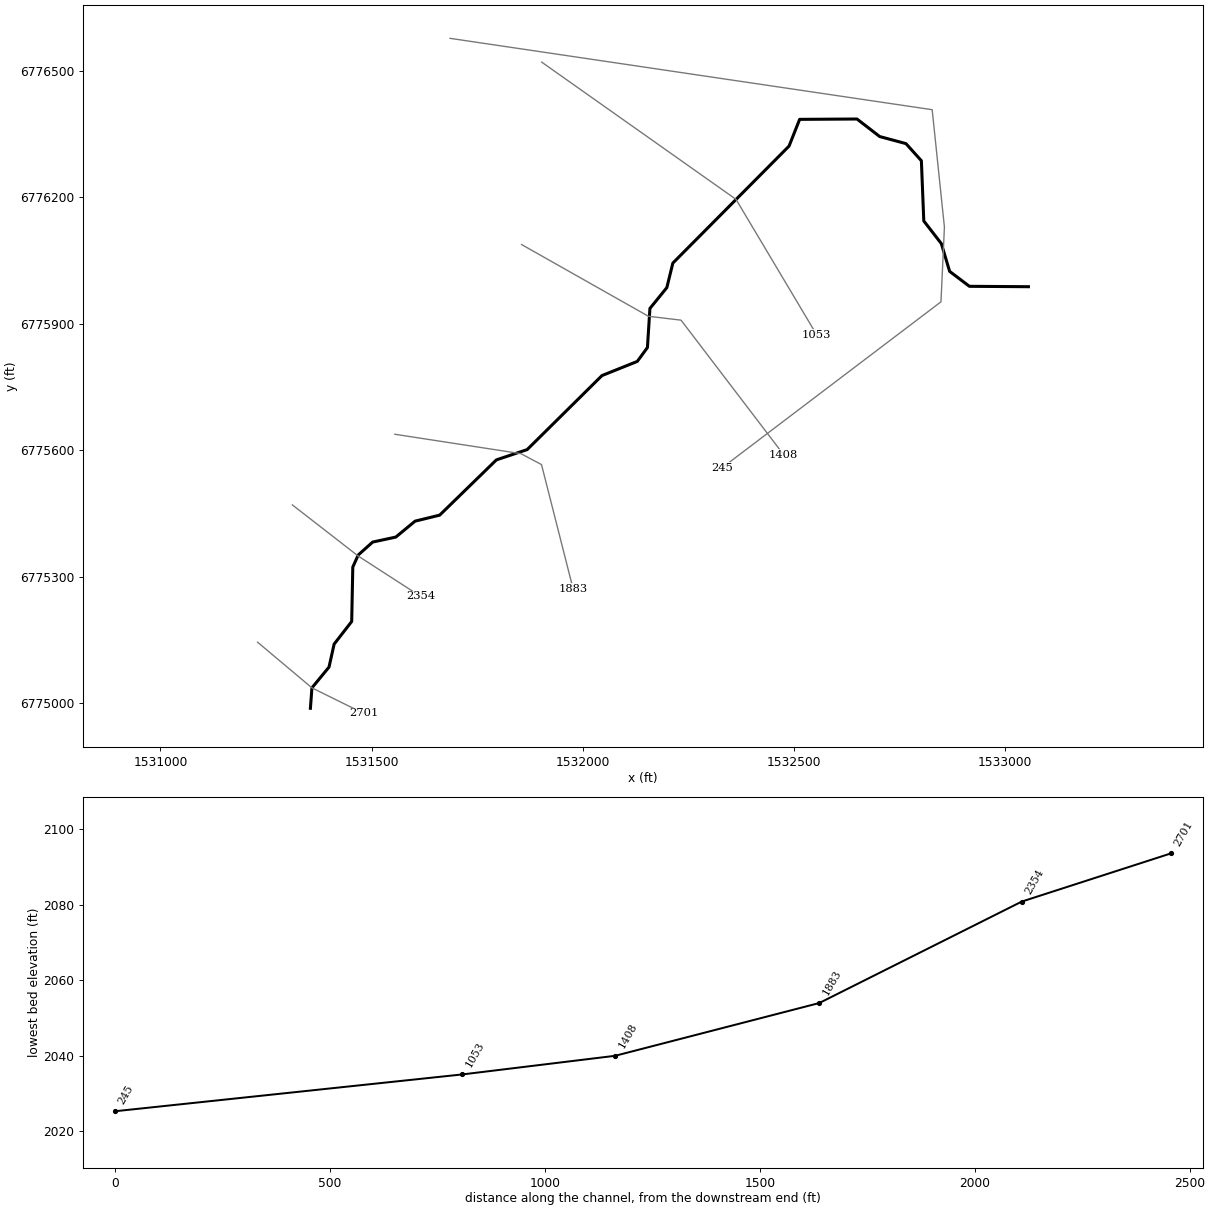
--- Elm 88.prj (project) ---

Proj Title=Elm 88 Base Level Engineering
Current Plan=p01
Default Exp/Contr=0.3,0.1
English Units
Geom File=g01
Flow File=f01
Plan File=p01
BEGIN DESCRIPTION:
Elm 88
END DESCRIPTION:

--- Elm 88.p01 (plan) ---

Plan Title=Multiple Run
Short Identifier=Multiple
Geom File=g01
Flow File=f01
Subcritical Flow
K Sum by GR= 0
Std Step Tol= 0.01
Critical Tol= 0.01
Num of Std Step Trials= 20
Max Error Tol= 0.3
Flow Tol Ratio= 0.001
Split Flow NTrial= 30
Split Flow Tol= 0.02
Split Flow Ratio= 0.02
Log Output Level= 0
Friction Slope Method= 1
Unsteady Friction Slope Method= 2
Unsteady Bridges Friction Slope Method= 1
Parabolic Critical Depth
Global Vel Dist=  1 , 1 , 1
Global Log Level= 0
CheckData=True
Encroach Param= -1, 0, 0, 0
BEGIN DESCRIPTION:
Multiple Run
END DESCRIPTION:

--- Elm 88.f01 (steady flow) ---

Flow Title=Multiple
Number of Profiles=7
Profile Names=10-year,25-year,50-year,1pct_min,100-year,1pct_plu,500-year
River Rch & RM= Elm 88,Reach-1,2701
      95     125     149     111     178     245     257
Boundary for River Rch & Prof#=Elm 88,Reach-1,1
Up Type=0
Dn Type=3
Dn Slope=0.005
Boundary for River Rch & Prof#=Elm 88,Reach-1,2
Up Type=0
Dn Type=3
Dn Slope=0.005
Boundary for River Rch & Prof#=Elm 88,Reach-1,3
Up Type=0
Dn Type=3
Dn Slope=0.005
Boundary for River Rch & Prof#=Elm 88,Reach-1,4
Up Type=0
Dn Type=3
Dn Slope=0.005
Boundary for River Rch & Prof#=Elm 88,Reach-1,5
Up Type=0
Dn Type=3
Dn Slope=0.005
Boundary for River Rch & Prof#=Elm 88,Reach-1,6
Up Type=0
Dn Type=3
Dn Slope=0.005
Boundary for River Rch & Prof#=Elm 88,Reach-1,7
Up Type=0
Dn Type=3
Dn Slope=0.005

--- Elm 88.g01 (geometry) ---

Geom Title=Existing Conditions

River Reach=Elm 88,Reach-1
Reach XY= 30
      1531355.00      6774988.00      1531358.60      6775036.51
      1531399.05      6775085.75      1531411.11      6775140.19
      1531452.75      6775193.93      1531455.34      6775322.96
      1531468.23      6775351.67      1531502.42      6775382.29
      1531557.16      6775394.11      1531602.81      6775431.90
      1531661.06      6775446.14      1531795.32      6775577.22
      1531868.21      6775601.63      1532045.34      6775777.21
      1532128.95      6775810.81      1532152.92      6775843.71
      1532158.83      6775936.41      1532198.86      6775985.83
      1532213.14      6776044.06      1532488.26      6776321.55
      1532513.31      6776384.94      1532649.06      6776385.78
      1532702.86      6776344.15      1532765.06      6776327.39
      1532801.55      6776286.75      1532807.25      6776143.93
      1532848.85      6776090.14      1532868.44      6776024.36
      1532915.25      6775988.92      1533055.00      6775988.00

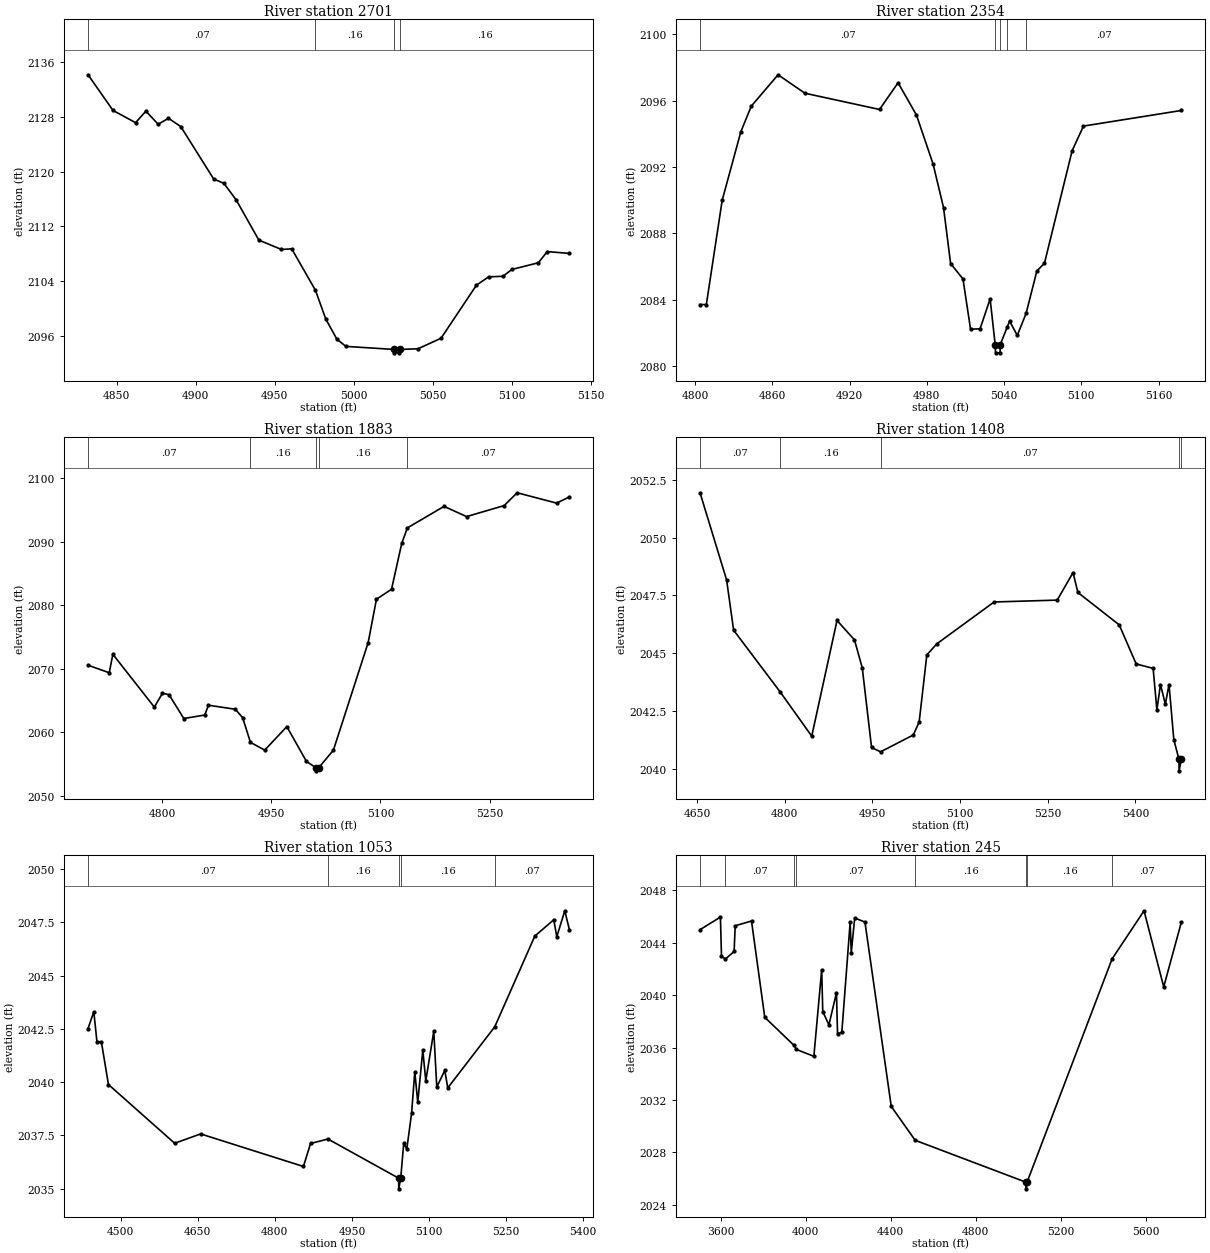
Type RM Length L Ch R = 1,2701,347,347,347
BEGIN DESCRIPTION:
474
END DESCRIPTION:
XS GIS Cut Line= 3
      1531229.90      6775144.81      1531358.60      6775036.51
      1531480.82      6774975.95
#Sta/Elev= 30
  4831.8 2134.13  4847.6 2128.93  4861.9 2127.14  4868.4 2128.83  4876.2 2126.91
  4882.7 2127.79  4890.5 2126.57  4911.3 2118.93  4917.8 2118.29  4925.6 2115.86
  4939.9 2110.01  4954.2 2108.65  4960.7 2108.74  4975.7 2102.70  4982.2 2098.53
  4989.3 2095.55  4995.0 2094.51  5025.2 2094.07  5025.4 2093.57  5028.9 2093.57
  5029.2 2094.07  5040.6 2094.16  5055.2 2095.70  5077.6 2103.44  5085.3 2104.65
  5094.4 2104.74  5100.0 2105.73  5116.8 2106.71  5122.4 2108.34  5136.4 2108.07
#Mann=4,-1,0
  4831.8    0.07       0  4975.7    0.16       0  5025.2    0.07       0
  5029.2    0.16       0
Bank Sta=5025.2,5029.2
Exp/Cntr=0.3,0.1

Type RM Length L Ch R = 1,2354,471,471,471
BEGIN DESCRIPTION:
804
END DESCRIPTION:
XS GIS Cut Line= 3
      1531312.32      6775470.37      1531468.60      6775348.82
      1531616.21      6775253.30
#Sta/Elev= 30
  4803.9 2083.71  4808.8 2083.71  4821.1 2089.99  4835.6 2094.12  4843.7 2095.66
  4864.5 2097.55  4885.3 2096.44  4943.3 2095.46  4957.7 2097.07  4972.0 2095.12
  4984.9 2092.17  4993.0 2089.55  4998.5 2086.18  5008.1 2085.25  5014.0 2082.22
  5021.4 2082.25  5029.2 2084.05  5033.1 2081.30  5033.4 2080.80  5036.9 2080.80
  5037.1 2081.30  5042.6 2082.38  5044.3 2082.71  5050.3 2081.85  5057.1 2083.17
  5065.5 2085.73  5071.4 2086.20  5092.9 2092.98  5101.7 2094.46  5177.7 2095.40
#Mann=5,-1,0
  4803.9    0.07       0  5033.1    0.07       0  5037.1    0.07       0
  5042.6    0.16       0  5057.1    0.07       0
Bank Sta=5033.1,5037.1
Exp/Cntr=0.3,0.1

Type RM Length L Ch R = 1,1883,475,475,475
BEGIN DESCRIPTION:
473
END DESCRIPTION:
XS GIS Cut Line= 4
      1531554.98      6775638.00      1531853.35      6775591.98
      1531902.16      6775566.06      1531977.01      6775271.07
#Sta/Elev= 30
  4698.1 2070.55  4727.2 2069.36  4732.2 2072.27  4789.2 2063.95  4800.4 2066.13
  4809.4 2065.91  4829.7 2062.15  4858.5 2062.70  4863.6 2064.25  4900.5 2063.61
  4910.6 2062.28  4921.3 2058.39  4941.0 2057.18  4971.3 2060.88  4998.3 2055.39
  5011.2 2054.41  5011.4 2053.91  5015.2 2054.41  5035.3 2057.16  5083.1 2074.12
  5094.5 2080.95  5115.2 2082.51  5129.2 2089.73  5137.0 2092.18  5187.4 2095.57
  5218.3 2093.96  5269.9 2095.69  5287.9 2097.71  5342.1 2096.08  5359.6 2097.05
#Mann=5,-1,0
  4698.1    0.07       0  4921.3    0.16       0  5011.2    0.07       0
  5015.2    0.16       0  5137.0    0.07       0
Bank Sta=5011.2,5015.2
Exp/Cntr=0.3,0.1

Type RM Length L Ch R = 1,1408,355,355,355
BEGIN DESCRIPTION:
472
END DESCRIPTION:
XS GIS Cut Line= 4
      1531854.98      6776088.01      1532155.24      6775917.89
      1532232.54      6775908.64      1532475.37      6775589.59
#Sta/Elev= 30
  4654.9 2051.94  4700.4 2048.17  4712.4 2046.00  4792.4 2043.32  4846.1 2041.42
  4889.4 2046.42  4919.3 2045.58  4932.6 2044.37  4948.5 2040.93  4963.9 2040.74
  5019.9 2041.47  5030.0 2042.03  5043.1 2044.93  5060.2 2045.41  5158.3 2047.22
  5266.3 2047.30  5293.4 2048.49  5301.7 2047.63  5372.4 2046.23  5401.5 2044.54
  5430.5 2044.35  5436.9 2042.56  5443.1 2043.65  5451.4 2042.80  5457.7 2043.65
  5465.9 2041.27  5474.7 2040.42  5474.9 2039.92  5478.7 2040.42  5478.8 2040.42
#Mann=5,-1,0
  4654.9    0.07       0  4792.4    0.16       0  4963.9    0.07       0
  5474.7    0.07       0  5478.7    0.07       0
Bank Sta=5474.7,5478.7
Exp/Cntr=0.3,0.1

Type RM Length L Ch R = 1,1053,808,808,808
BEGIN DESCRIPTION:
803
END DESCRIPTION:
XS GIS Cut Line= 3
      1531902.61      6776520.70      1532362.70      6776195.17
      1532553.68      6775873.97
#Sta/Elev= 30
  4436.2 2042.52  4447.4 2043.31  4453.5 2041.91  4462.2 2041.89  4475.9 2039.89
  4604.9 2037.13  4655.4 2037.57  4855.6 2036.04  4869.5 2037.12  4903.4 2037.33
  5041.1 2035.49  5041.3 2034.99  5045.1 2035.49  5051.0 2037.14  5056.9 2036.85
  5066.3 2038.55  5072.5 2040.48  5078.3 2039.06  5088.1 2041.50  5093.9 2040.06
  5109.5 2042.39  5115.3 2039.77  5130.9 2040.55  5136.7 2039.73  5228.2 2042.60
  5306.2 2046.86  5343.2 2047.63  5349.0 2046.83  5364.6 2048.05  5373.5 2047.17
#Mann=5,-1,0
  4436.2    0.07       0  4903.4    0.16       0  5041.1    0.07       0
  5045.1    0.16       0  5228.2    0.07       0
Bank Sta=5041.1,5045.1
Exp/Cntr=0.3,0.1

Type RM Length L Ch R = 1,245,0,0,0
BEGIN DESCRIPTION:
471
END DESCRIPTION:
XS GIS Cut Line= 5
      1531685.59      6776577.12      1532827.11      6776407.84
      1532856.09      6776129.32      1532847.92      6775952.15
      1532328.98      6775557.91
#Sta/Elev= 30
  3503.2 2044.98  3599.0 2045.94  3604.1 2042.96  3622.4 2042.74  3663.5 2043.32
  3668.5 2045.28  3745.2 2045.64  3807.5 2038.30  3944.0 2036.18  3956.5 2035.85
  4038.4 2035.33  4075.2 2041.92  4080.3 2038.74  4109.2 2037.73  4144.7 2040.18
  4149.7 2037.06  4169.8 2037.15  4209.1 2045.54  4214.2 2043.24  4230.5 2045.87
  4278.6 2045.56  4402.3 2031.51  4514.7 2028.93  5036.7 2025.73  5036.9 2025.23
  5040.7 2025.73  5440.5 2042.75  5590.9 2046.42  5683.4 2040.62  5766.3 2045.55
#Mann=8,-1,0
  3503.2   0.035       0  3622.4    0.07       0  3944.0   0.035       0
  3956.5    0.07       0  4514.7    0.16       0  5036.7    0.07       0
  5040.7    0.16       0  5440.5    0.07       0
Bank Sta=5036.7,5040.7
Exp/Cntr=0.3,0.1

Chan Stop Cuts=-1