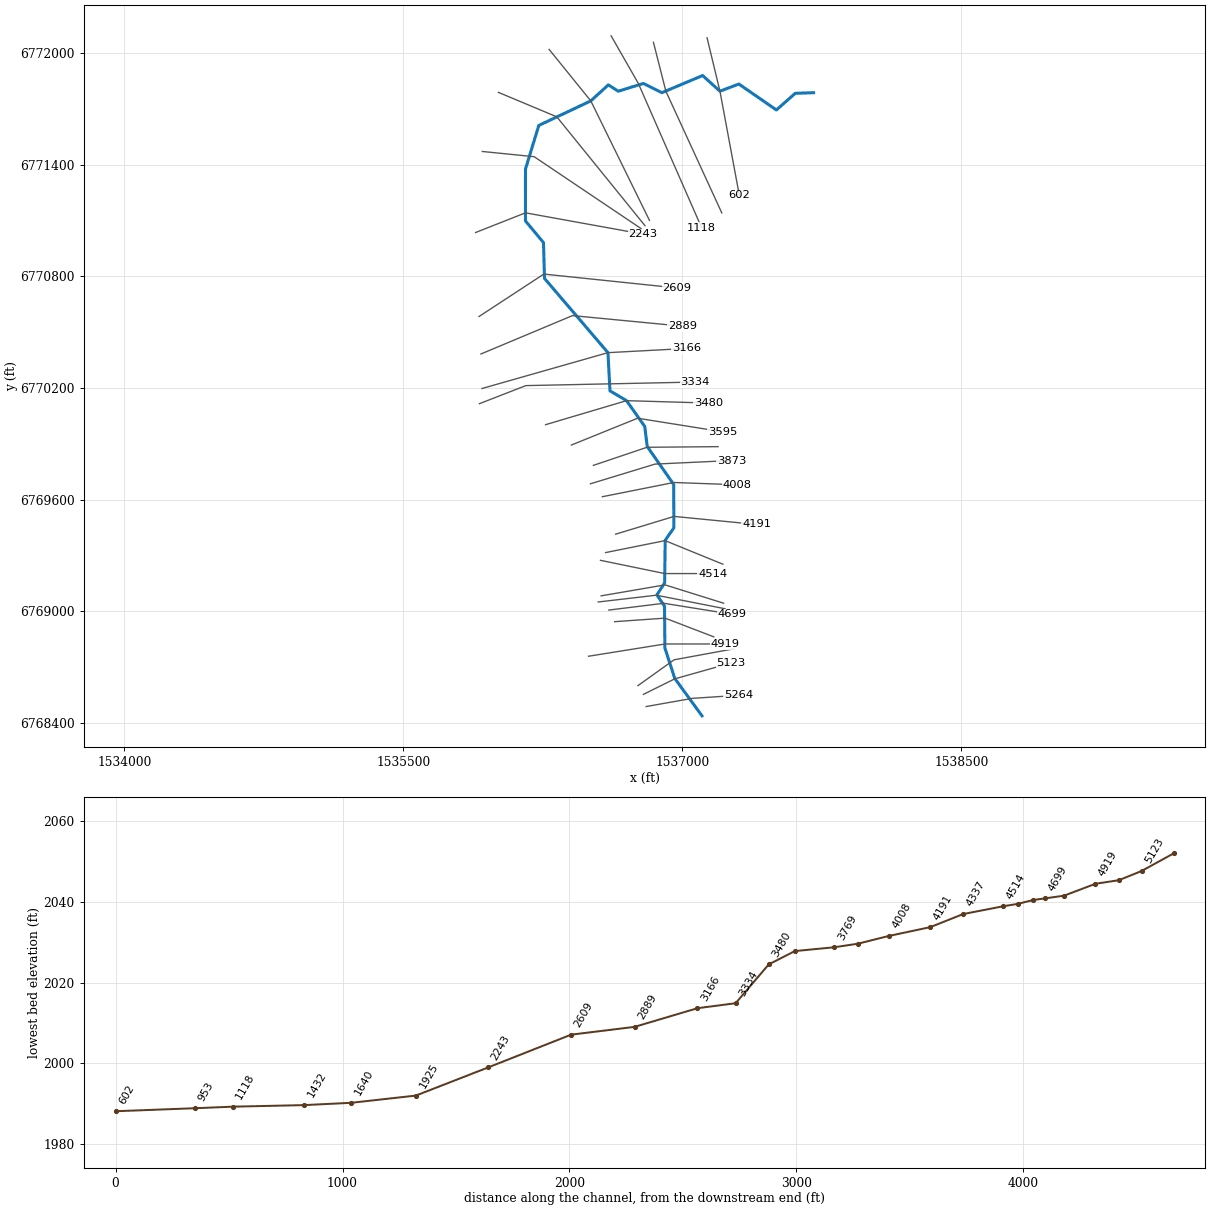
--- Elm 89.prj (project) ---

Proj Title=Elm 89 Base Level Engineering
Current Plan=p01
Default Exp/Contr=0.3,0.1
English Units
Geom File=g01
Flow File=f01
Plan File=p01
BEGIN DESCRIPTION:
Elm 89
END DESCRIPTION:

--- Elm 89.p01 (plan) ---

Plan Title=Multiple Run
Short Identifier=Multiple
Geom File=g01
Flow File=f01
Subcritical Flow
K Sum by GR= 0
Std Step Tol= 0.01
Critical Tol= 0.01
Num of Std Step Trials= 20
Max Error Tol= 0.3
Flow Tol Ratio= 0.001
Split Flow NTrial= 30
Split Flow Tol= 0.02
Split Flow Ratio= 0.02
Log Output Level= 0
Friction Slope Method= 1
Unsteady Friction Slope Method= 2
Unsteady Bridges Friction Slope Method= 1
Parabolic Critical Depth
Global Vel Dist=  1 , 1 , 1
Global Log Level= 0
CheckData=True
Encroach Param= -1, 0, 0, 0
BEGIN DESCRIPTION:
Multiple Run
END DESCRIPTION:

--- Elm 89.f01 (steady flow) ---

Flow Title=Multiple
Number of Profiles=7
Profile Names=10-year,25-year,50-year,1pct_min,100-year,1pct_plu,500-year
River Rch & RM= Elm 89,Reach-1,5264
     163     222     270     204     327     450     488
Boundary for River Rch & Prof#=Elm 89,Reach-1,1
Up Type=0
Dn Type=3
Dn Slope=0.005
Boundary for River Rch & Prof#=Elm 89,Reach-1,2
Up Type=0
Dn Type=3
Dn Slope=0.005
Boundary for River Rch & Prof#=Elm 89,Reach-1,3
Up Type=0
Dn Type=3
Dn Slope=0.005
Boundary for River Rch & Prof#=Elm 89,Reach-1,4
Up Type=0
Dn Type=3
Dn Slope=0.005
Boundary for River Rch & Prof#=Elm 89,Reach-1,5
Up Type=0
Dn Type=3
Dn Slope=0.005
Boundary for River Rch & Prof#=Elm 89,Reach-1,6
Up Type=0
Dn Type=3
Dn Slope=0.005
Boundary for River Rch & Prof#=Elm 89,Reach-1,7
Up Type=0
Dn Type=3
Dn Slope=0.005

--- Elm 89.g01 (geometry) ---

Geom Title=Existing Conditions

River Reach=Elm 89,Reach-1
Reach XY= 30
      1537105.00      6768438.00      1536958.62      6768639.50
      1536905.52      6768803.22      1536903.62      6769027.56
      1536862.56      6769088.00      1536904.34      6769153.16
      1536907.26      6769382.06      1536953.78      6769448.50
      1536952.94      6769682.14      1536810.77      6769885.68
      1536797.12      6769994.17      1536699.35      6770132.36
      1536610.39      6770185.32      1536599.54      6770390.45
      1536258.54      6770789.46      1536252.93      6770982.14
      1536156.06      6771098.44      1536156.22      6771377.50
      1536227.70      6771611.90      1536507.30      6771743.86
      1536601.67      6771829.99      1536654.90      6771795.81
      1536789.73      6771837.60      1536889.61      6771788.09
      1537108.42      6771880.18      1537201.59      6771795.85
      1537303.26      6771834.63      1537505.00      6771695.09
      1537606.40      6771784.59      1537705.00      6771788.00

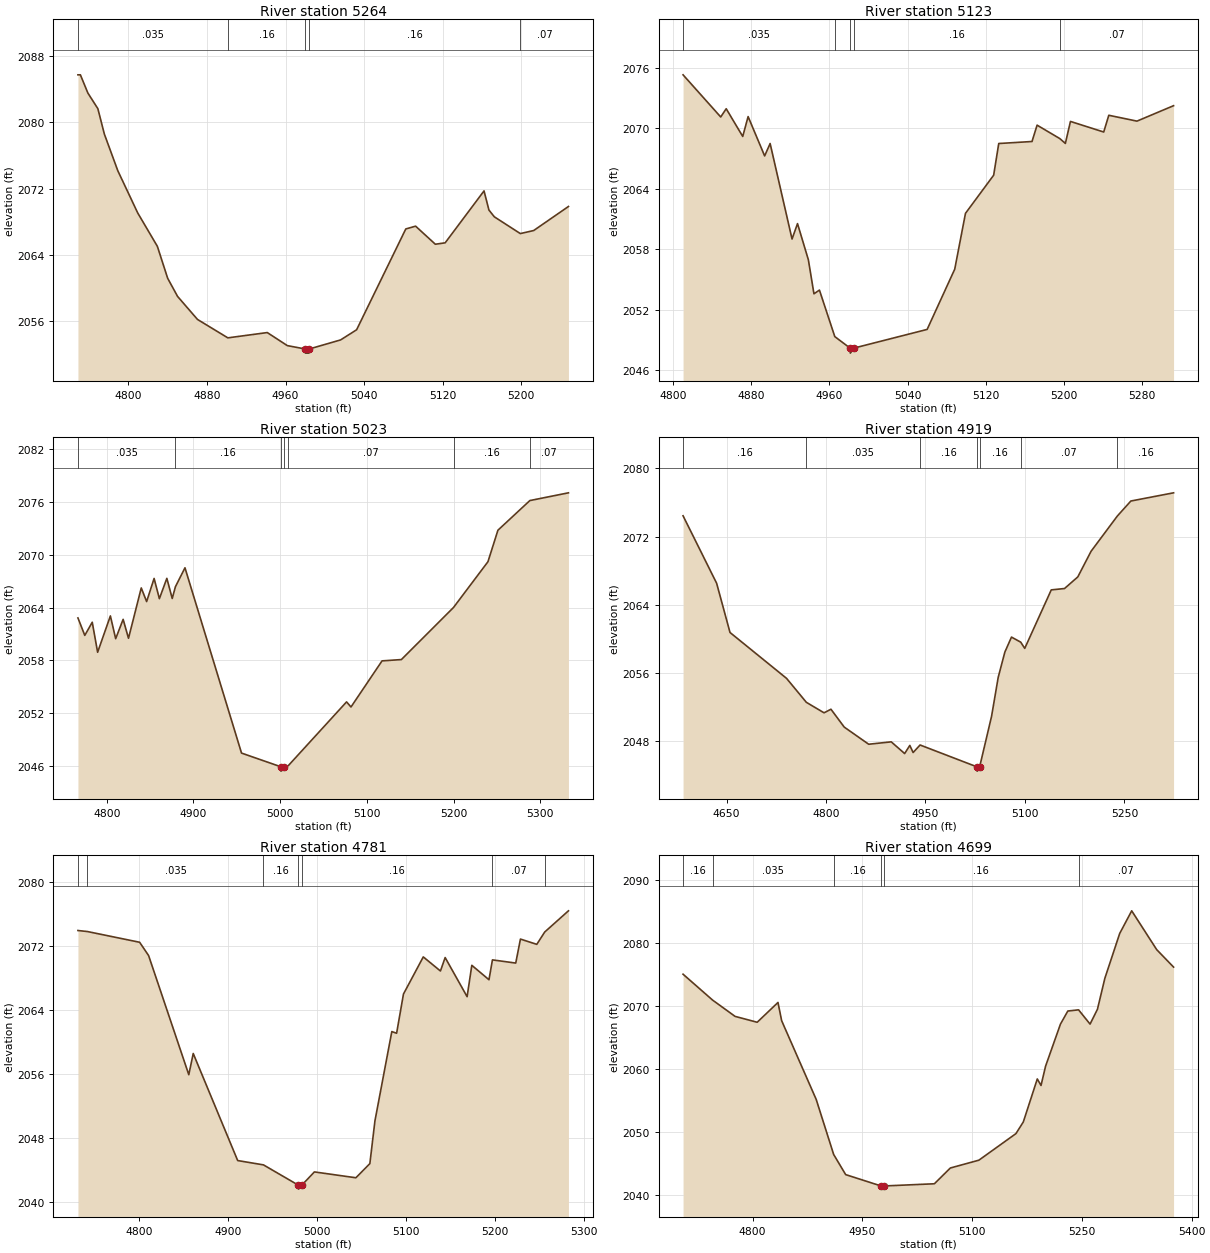
Type RM Length L Ch R = 1,5264,141,141,141
BEGIN DESCRIPTION:
Elm 89 5263.527
END DESCRIPTION:
XS GIS Cut Line= 3
      1536805.04      6768488.01      1537052.65      6768532.03
      1537300.31      6768548.36
#Sta/Elev= 30
  4748.5 2085.77  4751.0 2085.77  4758.6 2083.57  4768.8 2081.67  4775.4 2078.60
  4789.1 2074.16  4809.4 2069.04  4829.4 2065.00  4839.9 2061.13  4850.0 2058.93
  4870.3 2056.14  4901.2 2053.91  4941.4 2054.55  4961.8 2052.97  4980.1 2052.56
  4980.3 2052.06  4983.8 2052.06  4984.1 2052.56  5016.1 2053.66  5032.4 2054.89
  5082.5 2067.10  5092.5 2067.44  5112.6 2065.25  5122.6 2065.42  5162.2 2071.71
  5167.2 2069.39  5172.7 2068.57  5199.2 2066.54  5212.8 2066.91  5248.2 2069.82
#Mann=5,-1,0
  4748.5   0.035       0  4901.2    0.16       0  4980.1    0.07       0
  4984.1    0.16       0  5199.2    0.07       0
Bank Sta=4980.1,4984.1
Exp/Cntr=0.3,0.1

Type RM Length L Ch R = 1,5123,100,100,100
BEGIN DESCRIPTION:
Elm 89 5122.57
END DESCRIPTION:
XS GIS Cut Line= 3
      1536790.20      6768553.57      1536958.64      6768636.92
      1537260.36      6768721.89
#Sta/Elev= 30
  4810.5 2075.30  4849.0 2071.12  4854.6 2071.94  4871.5 2069.19  4877.0 2071.16
  4893.9 2067.26  4899.5 2068.49  4921.9 2059.02  4927.5 2060.55  4938.6 2056.96
  4944.3 2053.59  4949.9 2053.96  4965.6 2049.35  4981.2 2048.21  4981.5 2047.71
  4985.2 2048.21  5060.0 2050.06  5088.2 2056.03  5099.2 2061.57  5128.0 2065.35
  5133.2 2068.49  5167.2 2068.69  5172.4 2070.31  5195.6 2068.98  5201.3 2068.50
  5206.5 2070.68  5240.5 2069.63  5245.7 2071.29  5274.5 2070.71  5311.9 2072.24
#Mann=5,-1,0
  4810.5   0.035       0  4965.6    0.16       0  4981.2    0.07       0
  4985.2    0.16       0  5195.6    0.07       0
Bank Sta=4981.2,4985.2
Exp/Cntr=0.3,0.1

Type RM Length L Ch R = 1,5023,104,104,104
BEGIN DESCRIPTION:
Elm 89 5022.52
END DESCRIPTION:
XS GIS Cut Line= 3
      1536760.70      6768600.45      1536955.17      6768739.35
      1537276.31      6768798.38
#Sta/Elev= 30
  4766.8 2062.83  4774.7 2060.85  4783.3 2062.34  4789.5 2058.93  4804.2 2063.06
  4810.3 2060.47  4818.9 2062.67  4825.1 2060.52  4839.8 2066.24  4846.0 2064.69
  4854.6 2067.32  4860.7 2065.02  4869.3 2067.33  4875.5 2065.04  4879.2 2066.38
  4890.2 2068.53  4955.4 2047.47  5000.6 2045.92  5000.9 2045.42  5004.6 2045.92
  5009.3 2046.04  5076.5 2053.29  5081.6 2052.71  5117.4 2057.95  5139.7 2058.10
  5199.8 2064.02  5239.5 2069.22  5251.0 2072.80  5287.8 2076.17  5332.3 2077.05
#Mann=7,-1,0
  4766.8   0.035       0  4879.2    0.16       0  5000.6    0.07       0
  5004.6    0.16       0  5009.3    0.07       0  5199.8    0.16       0
  5287.8    0.07       0
Bank Sta=5000.6,5004.6
Exp/Cntr=0.3,0.1

Type RM Length L Ch R = 1,4919,138,138,138
BEGIN DESCRIPTION:
Elm 89 4919.43
END DESCRIPTION:
XS GIS Cut Line= 3
      1536495.08      6768758.45      1536906.56      6768824.42
      1537229.43      6768824.42
#Sta/Elev= 30
  4584.5 2074.43  4635.1 2066.53  4655.3 2060.76  4740.5 2055.39  4770.4 2052.58
  4797.1 2051.35  4807.5 2051.77  4827.5 2049.68  4864.4 2047.67  4898.4 2047.95
  4918.6 2046.58  4926.4 2047.53  4931.4 2046.70  4941.9 2047.58  5027.7 2045.02
  5027.9 2044.52  5031.7 2045.02  5049.7 2050.95  5059.7 2055.51  5069.7 2058.46
  5079.7 2060.22  5093.6 2059.63  5099.7 2058.90  5139.7 2065.75  5159.7 2065.91
  5179.7 2067.27  5199.7 2070.27  5239.3 2074.40  5259.7 2076.16  5324.1 2077.12
#Mann=7,-1,0
  4584.5    0.16       0  4770.4   0.035       0  4941.9    0.16       0
  5027.7    0.07       0  5031.7    0.16       0  5093.6    0.07       0
  5239.3    0.16       0
Bank Sta=5027.7,5031.7
Exp/Cntr=0.3,0.1

Type RM Length L Ch R = 1,4781,82,82,82
BEGIN DESCRIPTION:
Elm 89 4780.51
END DESCRIPTION:
XS GIS Cut Line= 3
      1536635.73      6768944.22      1536906.56      6768963.31
      1537168.22      6768862.81
#Sta/Elev= 30
  4730.9 2073.89  4741.6 2073.76  4800.3 2072.42  4810.4 2070.76  4855.6 2055.87
  4860.6 2058.52  4910.6 2045.14  4939.6 2044.60  4978.8 2042.07  4979.0 2041.57
  4982.8 2042.07  4996.9 2043.72  5043.6 2042.99  5059.3 2044.76  5065.0 2050.09
  5084.0 2061.26  5089.4 2061.05  5097.1 2065.95  5119.4 2070.59  5138.7 2068.83
  5144.0 2070.51  5168.7 2065.62  5174.0 2069.54  5193.3 2067.74  5197.2 2070.22
  5223.4 2069.82  5228.7 2072.82  5247.1 2072.16  5256.0 2073.70  5282.7 2076.35
#Mann=7,-1,0
  4730.9    0.16       0  4741.6   0.035       0  4939.6    0.16       0
  4978.8    0.07       0  4982.8    0.16       0  5197.2    0.07       0
  5256.0    0.16       0
Bank Sta=4978.8,4982.8
Exp/Cntr=0.3,0.1

Type RM Length L Ch R = 1,4699,54,54,54
BEGIN DESCRIPTION:
Elm 89 4699.46
END DESCRIPTION:
XS GIS Cut Line= 3
      1536604.43      6769006.71      1536899.61      6769043.17
      1537267.69      6768984.14
#Sta/Elev= 30
  4705.1 2075.00  4745.5 2070.89  4776.2 2068.31  4806.4 2067.38  4834.8 2070.52
  4839.8 2067.63  4887.0 2055.15  4910.9 2046.41  4927.3 2043.22  4975.7 2041.42
  4976.0 2040.92  4979.7 2041.42  5048.5 2041.77  5070.3 2044.27  5109.3 2045.51
  5159.9 2049.72  5170.0 2051.57  5189.1 2058.39  5194.2 2057.36  5200.4 2060.41
  5220.7 2067.07  5230.8 2069.16  5245.5 2069.35  5261.2 2067.09  5271.3 2069.44
  5281.4 2074.34  5301.7 2081.46  5318.1 2085.05  5352.3 2078.89  5375.3 2076.13
#Mann=6,-1,0
  4705.1    0.16       0  4745.5   0.035       0  4910.9    0.16       0
  4975.7    0.07       0  4979.7    0.16       0  5245.5    0.07       0
Bank Sta=4975.7,4979.7
Exp/Cntr=0.3,0.1

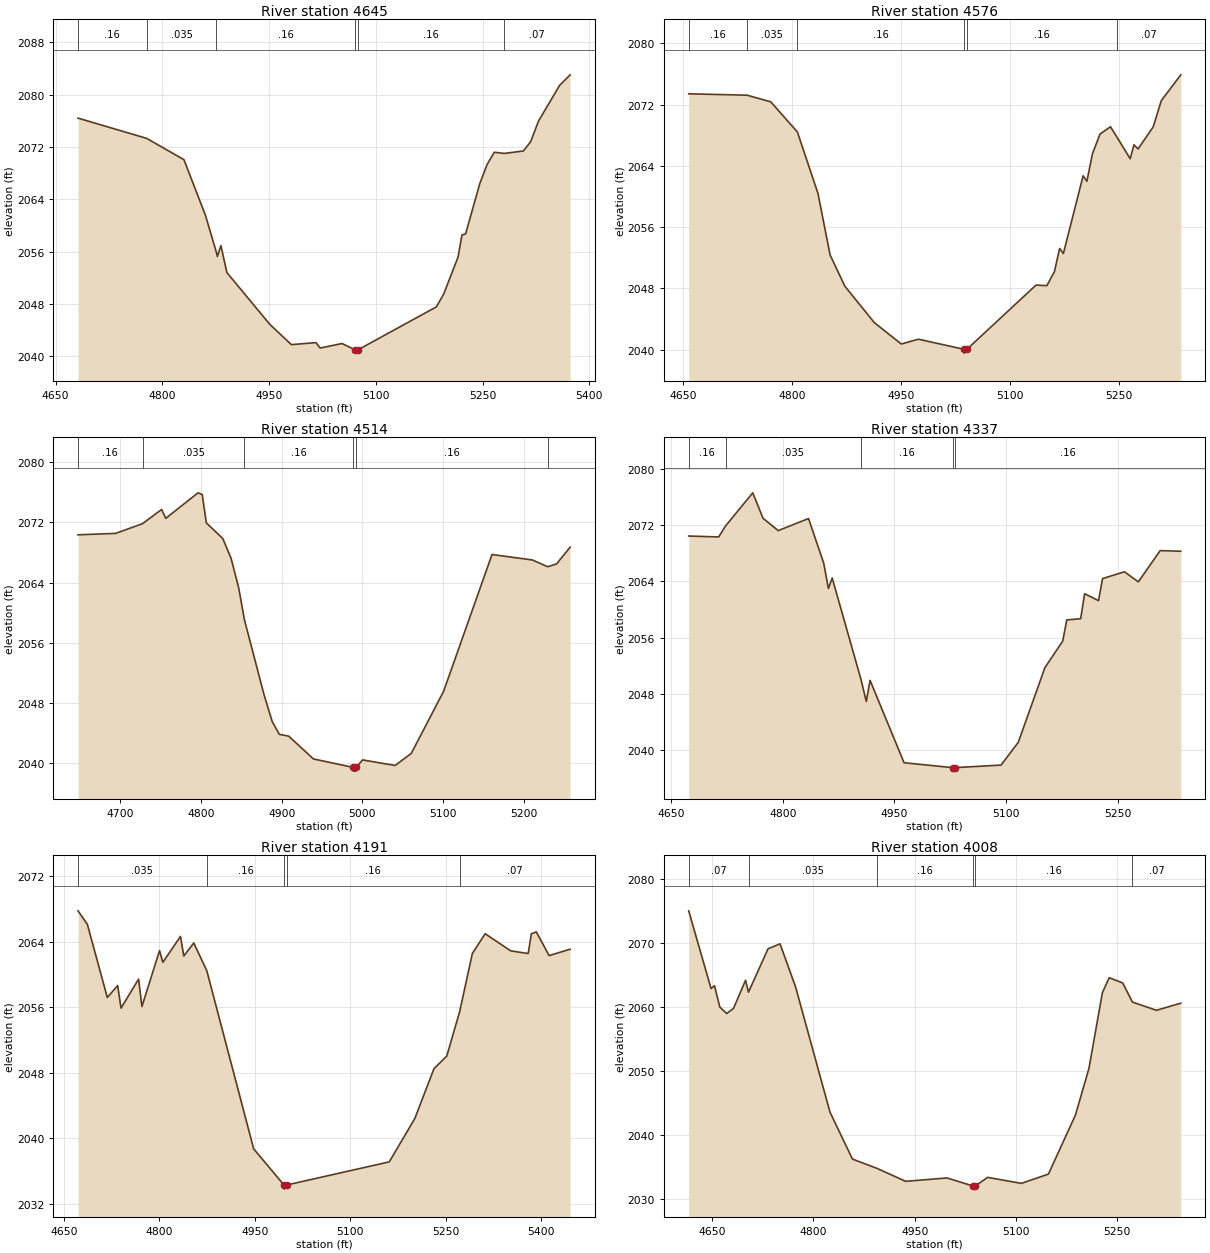
Type RM Length L Ch R = 1,4645,69,69,69
BEGIN DESCRIPTION:
Elm 89 4644.58
END DESCRIPTION:
XS GIS Cut Line= 3
      1536547.22      6769050.12      1536859.68      6769086.58
      1537229.48      6769013.66
#Sta/Elev= 30
  4681.4 2076.43  4777.9 2073.33  4830.2 2070.08  4860.4 2061.59  4875.8 2055.91
  4877.2 2055.27  4882.2 2056.93  4890.6 2052.81  4951.0 2044.88  4981.2 2041.79
  5015.6 2042.10  5021.8 2041.27  5052.4 2041.96  5070.7 2040.99  5071.0 2040.49
  5074.7 2040.99  5184.9 2047.56  5195.1 2049.49  5215.4 2055.17  5220.9 2058.56
  5226.0 2058.72  5246.0 2066.42  5256.2 2069.33  5266.4 2071.21  5280.4 2071.03
  5307.2 2071.40  5317.4 2072.82  5328.6 2076.00  5358.1 2081.43  5372.9 2083.05
#Mann=6,-1,0
  4681.4    0.16       0  4777.9   0.035       0  4875.8    0.16       0
  5070.7    0.07       0  5074.7    0.16       0  5280.4    0.07       0
Bank Sta=5070.7,5074.7
Exp/Cntr=0.3,0.1

Type RM Length L Ch R = 1,4576,62,62,62
BEGIN DESCRIPTION:
Elm 89 4576.02
END DESCRIPTION:
XS GIS Cut Line= 3
      1536562.82      6769083.11      1536906.56      6769142.13
      1537221.22      6769043.58
#Sta/Elev= 30
  4657.2 2073.40  4737.6 2073.22  4770.3 2072.36  4807.1 2068.41  4835.4 2060.40
  4852.2 2052.34  4872.5 2048.27  4913.1 2043.52  4950.3 2040.72  4973.9 2041.35
  5036.8 2040.03  5037.0 2039.53  5040.8 2040.03  5136.1 2048.42  5151.0 2048.34
  5161.5 2050.18  5168.6 2053.21  5173.8 2052.54  5201.0 2062.69  5206.2 2061.97
  5213.9 2065.58  5224.4 2068.15  5238.7 2069.10  5248.2 2067.66  5265.9 2064.92
  5271.1 2066.74  5276.8 2066.20  5297.7 2069.09  5308.8 2072.51  5335.7 2075.88
#Mann=6,-1,0
  4657.2    0.16       0  4737.6   0.035       0  4807.1    0.16       0
  5036.8    0.07       0  5040.8    0.16       0  5248.2    0.07       0
Bank Sta=5036.8,5040.8
Exp/Cntr=0.3,0.1

Type RM Length L Ch R = 1,4514,177,177,177
BEGIN DESCRIPTION:
Elm 89 4513.62
END DESCRIPTION:
XS GIS Cut Line= 3
      1536559.35      6769274.07      1536904.82      6769202.90
      1537161.79      6769202.90
#Sta/Elev= 30
  4647.7 2070.36  4694.3 2070.55  4727.6 2071.84  4751.3 2073.73  4756.4 2072.55
  4796.4 2075.94  4801.6 2075.71  4806.7 2071.94  4827.0 2069.88  4837.3 2067.25
  4846.8 2063.30  4853.9 2059.06  4878.1 2049.14  4888.3 2045.55  4897.1 2043.85
  4908.7 2043.61  4939.4 2040.58  4988.4 2039.46  4988.7 2038.96  4992.2 2038.96
  4992.4 2039.46  5000.2 2040.45  5040.6 2039.71  5060.6 2041.32  5100.6 2049.55
  5160.6 2067.74  5210.6 2067.02  5229.6 2066.12  5240.6 2066.49  5257.4 2068.72
#Mann=6,-1,0
  4647.7    0.16       0  4727.6   0.035       0  4853.9    0.16       0
  4988.4    0.07       0  4992.4    0.16       0  5229.6    0.07       0
Bank Sta=4988.4,4992.4
Exp/Cntr=0.3,0.1

Type RM Length L Ch R = 1,4337,146,146,146
BEGIN DESCRIPTION:
Elm 89 4336.71
END DESCRIPTION:
XS GIS Cut Line= 3
      1536587.08      6769315.74      1536906.56      6769379.98
      1537217.34      6769253.24
#Sta/Elev= 30
  4673.6 2070.43  4713.9 2070.30  4723.2 2071.87  4759.7 2076.57  4773.5 2072.96
  4793.9 2071.20  4834.7 2072.92  4855.1 2066.57  4861.4 2062.97  4866.5 2064.47
  4905.3 2050.01  4912.3 2046.93  4917.4 2049.92  4963.1 2038.21  5028.2 2037.52
  5028.4 2037.02  5032.2 2037.52  5093.5 2037.88  5116.6 2041.11  5152.4 2051.72
  5176.4 2055.51  5181.8 2058.51  5200.5 2058.68  5205.8 2062.23  5224.5 2061.25
  5229.9 2064.38  5259.3 2065.35  5278.0 2063.92  5307.4 2068.36  5335.1 2068.27
#Mann=5,-1,0
  4673.6    0.16       0  4723.2   0.035       0  4905.3    0.16       0
  5028.2    0.07       0  5032.2    0.16       0
Bank Sta=5028.2,5032.2
Exp/Cntr=0.3,0.1

Type RM Length L Ch R = 1,4191,183,183,183
BEGIN DESCRIPTION:
Elm 89 4191.01
END DESCRIPTION:
XS GIS Cut Line= 3
      1536640.94      6769414.70      1536955.17      6769510.19
      1537397.83      6769466.79
#Sta/Elev= 30
  4672.5 2067.77  4687.2 2066.12  4718.5 2057.18  4734.8 2058.64  4740.1 2055.88
  4767.7 2059.43  4772.9 2056.08  4800.6 2062.91  4805.8 2061.48  4833.5 2064.64
  4838.7 2062.25  4854.4 2063.84  4874.8 2060.46  4948.5 2038.68  4996.2 2034.26
  4996.5 2033.76  5000.2 2034.26  5161.5 2037.09  5201.7 2042.39  5231.8 2048.48
  5251.9 2050.02  5272.1 2055.44  5292.1 2062.56  5312.2 2064.97  5352.4 2062.88
  5379.8 2062.55  5384.8 2064.96  5392.6 2065.20  5412.7 2062.30  5445.7 2063.08
#Mann=5,-1,0
  4672.5   0.035       0  4874.8    0.16       0  4996.2    0.07       0
  5000.2    0.16       0  5272.1    0.07       0
Bank Sta=4996.2,5000.2
Exp/Cntr=0.3,0.1

Type RM Length L Ch R = 1,4008,135,135,135
BEGIN DESCRIPTION:
Elm 89 4007.9
END DESCRIPTION:
XS GIS Cut Line= 3
      1536569.76      6769616.09      1536953.43      6769692.48
      1537291.01      6769680.36
#Sta/Elev= 30
  4615.2 2075.09  4648.3 2062.93  4653.4 2063.38  4661.3 2060.04  4671.5 2059.03
  4681.7 2059.85  4699.4 2064.23  4703.8 2062.37  4732.7 2069.15  4750.5 2069.93
  4773.5 2063.20  4824.5 2043.61  4857.8 2036.27  4894.1 2034.82  4936.6 2032.79
  4997.8 2033.32  5036.0 2032.07  5036.2 2031.57  5040.0 2032.07  5058.0 2033.41
  5108.0 2032.47  5148.1 2033.92  5188.1 2043.15  5208.1 2050.44  5228.1 2062.31
  5238.1 2064.63  5258.1 2063.81  5272.6 2060.82  5308.2 2059.53  5344.2 2060.65
#Mann=6,-1,0
  4615.2    0.07       0  4703.8   0.035       0  4894.1    0.16       0
  5036.0    0.07       0  5040.0    0.16       0  5272.6    0.07       0
Bank Sta=5036,5040
Exp/Cntr=0.3,0.1

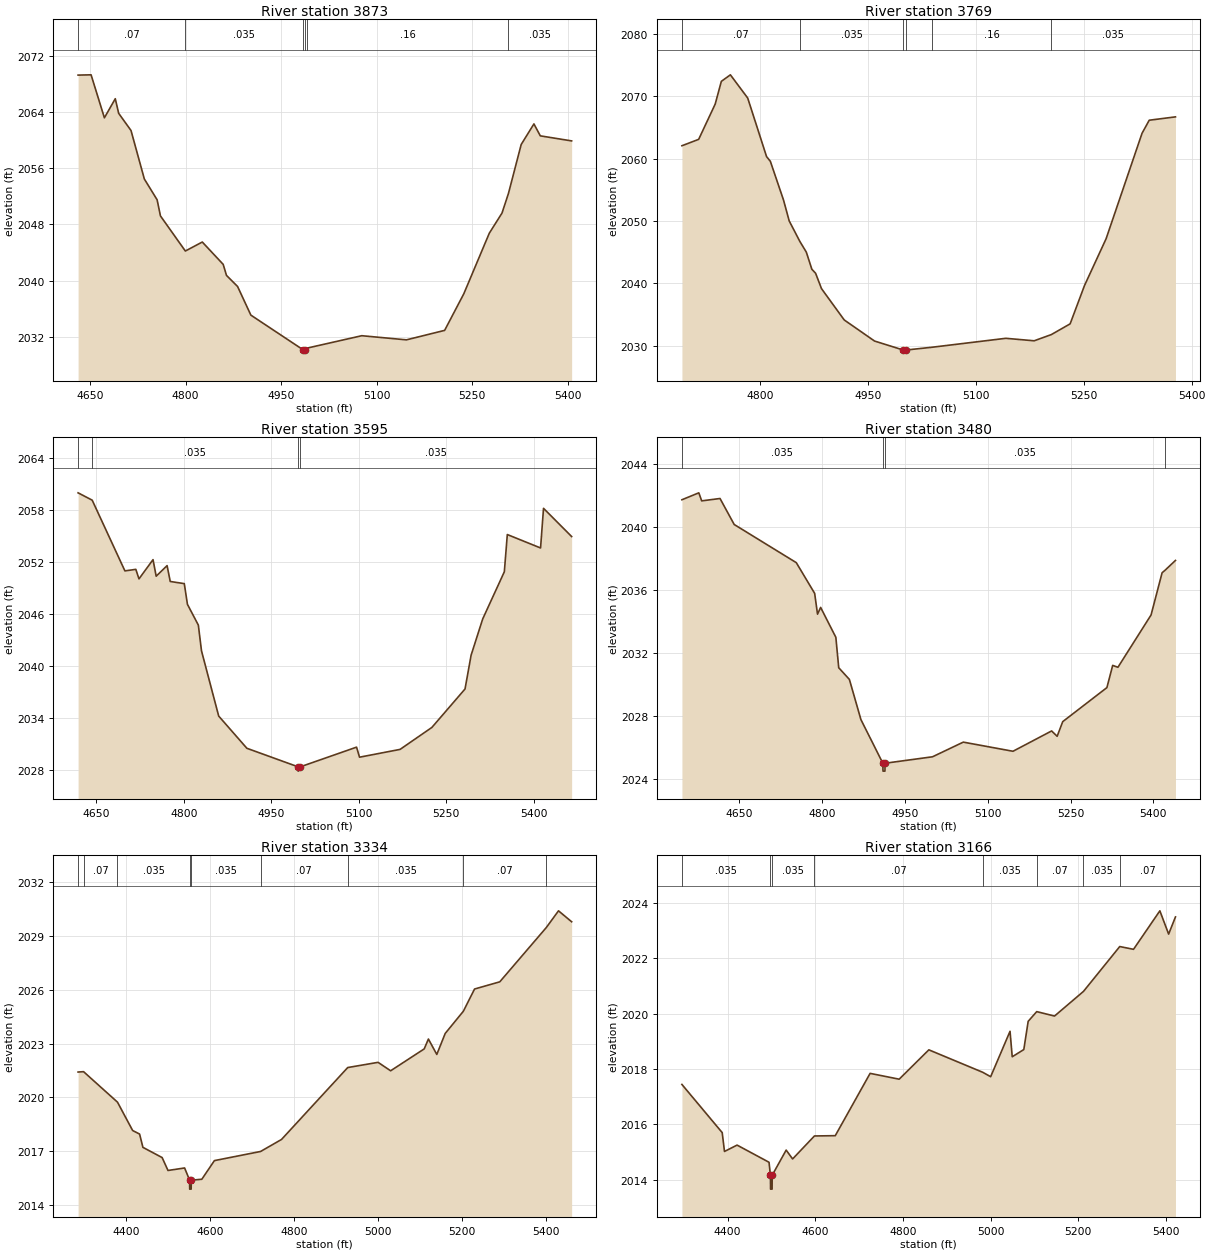
Type RM Length L Ch R = 1,3873,104,104,104
BEGIN DESCRIPTION:
Elm 89 3873.2
END DESCRIPTION:
XS GIS Cut Line= 3
      1536505.49      6769685.53      1536852.74      6769791.44
      1537264.16      6769810.53
#Sta/Elev= 30
  4631.1 2069.25  4651.5 2069.29  4672.4 2063.17  4689.5 2065.89  4694.8 2063.81
  4714.2 2061.36  4735.1 2054.46  4755.2 2051.49  4760.4 2049.20  4799.5 2044.20
  4826.1 2045.48  4858.9 2042.30  4864.1 2040.73  4881.5 2039.15  4902.4 2035.07
  4984.0 2030.16  4984.3 2029.66  4988.0 2030.16  4989.9 2030.36  5076.5 2032.14
  5146.6 2031.55  5206.6 2032.90  5236.7 2038.11  5276.7 2046.73  5296.7 2049.61
  5306.8 2052.40  5326.8 2059.37  5346.8 2062.30  5356.8 2060.60  5406.0 2059.88
#Mann=6,-1,0
  4631.1    0.07       0  4799.5   0.035       0  4984.0    0.07       0
  4988.0   0.035       0  4989.9    0.16       0  5306.8   0.035       0
Bank Sta=4984,4988
Exp/Cntr=0.3,0.1

Type RM Length L Ch R = 1,3769,174,174,174
BEGIN DESCRIPTION:
Elm 89 3769.46
END DESCRIPTION:
XS GIS Cut Line= 3
      1536521.11      6769784.48      1536809.34      6769881.72
      1537191.54      6769885.17
#Sta/Elev= 30
  4691.1 2062.08  4714.4 2063.11  4737.4 2068.78  4745.9 2072.42  4758.5 2073.47
  4782.6 2069.74  4808.8 2060.34  4814.1 2059.58  4832.4 2053.36  4840.3 2050.01
  4855.1 2046.72  4864.1 2045.00  4871.8 2042.25  4877.0 2041.61  4885.2 2039.14
  4916.8 2034.11  4959.0 2030.72  4998.9 2029.28  4999.2 2028.78  5002.9 2029.28
  5038.7 2029.72  5141.6 2031.16  5181.0 2030.76  5204.9 2031.76  5231.0 2033.48
  5251.0 2039.64  5281.0 2047.14  5331.0 2064.08  5341.0 2066.18  5377.5 2066.72
#Mann=6,-1,0
  4691.1    0.07       0  4855.1   0.035       0  4998.9   0.035       0
  5002.9   0.035       0  5038.7    0.16       0  5204.9   0.035       0
Bank Sta=4998.9,5002.9
Exp/Cntr=0.3,0.1

Type RM Length L Ch R = 1,3595,115,115,115
BEGIN DESCRIPTION:
Elm 89 3594.93
END DESCRIPTION:
XS GIS Cut Line= 3
      1536403.09      6769893.87      1536758.99      6770037.97
      1537215.54      6769965.06
#Sta/Elev= 30
  4618.8 2059.98  4643.0 2059.13  4699.1 2050.96  4717.8 2051.14  4723.2 2050.04
  4747.3 2052.26  4752.7 2050.35  4771.4 2051.57  4776.8 2049.74  4800.9 2049.49
  4806.3 2047.10  4825.0 2044.70  4830.4 2041.73  4859.9 2034.19  4908.2 2030.47
  4995.9 2028.33  4996.2 2027.83  4999.9 2028.33  5096.3 2030.60  5101.4 2029.44
  5170.9 2030.34  5225.5 2032.88  5282.3 2037.32  5292.7 2041.22  5312.6 2045.41
  5349.7 2050.86  5354.8 2055.16  5411.8 2053.61  5416.9 2058.19  5465.1 2054.93
#Mann=4,-1,0
  4618.8    0.07       0  4643.0   0.035       0  4995.9   0.035       0
  4999.9   0.035       0
Bank Sta=4995.9,4999.9
Exp/Cntr=0.3,0.1

Type RM Length L Ch R = 1,3480,146,146,146
BEGIN DESCRIPTION:
Elm 89 3399.308
END DESCRIPTION:
XS GIS Cut Line= 3
      1536264.20      6770003.24      1536699.35      6770132.36
      1537139.16      6770119.56
#Sta/Elev= 30
  4546.1 2041.75  4576.7 2042.19  4581.9 2041.68  4615.1 2041.83  4640.8 2040.18
  4753.2 2037.76  4786.5 2035.81  4791.7 2034.49  4797.3 2034.92  4824.9 2033.02
  4830.1 2031.09  4849.4 2030.35  4870.3 2027.80  4910.0 2025.03  4910.3 2024.53
  4913.8 2024.53  4914.0 2025.03  5000.0 2025.44  5055.7 2026.37  5145.7 2025.79
  5215.7 2027.08  5225.7 2026.74  5235.8 2027.67  5315.8 2029.83  5326.3 2031.24
  5335.8 2031.12  5395.8 2034.44  5415.8 2037.12  5420.6 2037.26  5440.0 2037.90
#Mann=4,-1,0
  4546.1   0.035       0  4910.0   0.035       0  4914.0   0.035       0
  5420.6    0.07       0
Bank Sta=4910,4914
Exp/Cntr=0.3,0.1

Type RM Length L Ch R = 1,3334,168,168,168
BEGIN DESCRIPTION:
Elm 89 4008
END DESCRIPTION:
XS GIS Cut Line= 3
      1535908.34      6770116.11      1536158.29      6770213.31
      1537066.30      6770232.41
#Sta/Elev= 30
  4285.3 2021.42  4298.4 2021.44  4379.2 2019.74  4415.3 2018.16  4431.9 2017.96
  4439.8 2017.22  4485.6 2016.65  4499.6 2015.93  4539.2 2016.07  4551.1 2015.39
  4551.3 2014.89  4554.8 2014.89  4555.1 2015.39  4580.2 2015.44  4610.2 2016.48
  4720.3 2016.99  4770.2 2017.66  4928.0 2021.67  5000.3 2021.96  5030.3 2021.49
  5110.3 2022.71  5120.3 2023.26  5140.3 2022.40  5160.3 2023.57  5203.6 2024.81
  5230.3 2026.05  5290.4 2026.45  5401.4 2029.48  5430.4 2030.41  5461.7 2029.80
#Mann=9,-1,0
  4285.3   0.035       0  4298.4    0.07       0  4379.2   0.035       0
  4551.1   0.035       0  4555.1   0.035       0  4720.3    0.07       0
  4928.0   0.035       0  5203.6    0.07       0  5401.4   0.035       0
Bank Sta=4551.1,4555.1
Exp/Cntr=0.3,0.1

Type RM Length L Ch R = 1,3166,277,277,277
BEGIN DESCRIPTION:
Elm 89 4009
END DESCRIPTION:
XS GIS Cut Line= 3
      1535922.14      6770197.67      1536599.54      6770390.45
      1537020.54      6770412.93
#Sta/Elev= 30
  4295.7 2017.44  4387.6 2015.70  4392.8 2015.02  4421.5 2015.25  4494.4 2014.63
  4497.6 2014.16  4497.9 2013.66  4501.4 2013.66  4501.6 2014.16  4533.5 2015.07
  4548.2 2014.75  4598.0 2015.58  4645.5 2015.59  4725.0 2017.84  4791.3 2017.63
  4859.0 2018.69  4981.8 2017.88  5000.0 2017.72  5044.2 2019.36  5049.2 2018.44
  5075.6 2018.70  5085.6 2019.72  5105.1 2020.07  5145.7 2019.91  5211.7 2020.80
  5294.5 2022.42  5325.9 2022.32  5386.0 2023.71  5406.0 2022.87  5421.6 2023.49
#Mann=8,-1,0
  4295.7   0.035       0  4497.6   0.035       0  4501.6   0.035       0
  4598.0    0.07       0  4981.8   0.035       0  5105.1    0.07       0
  5211.7   0.035       0  5294.5    0.07       0
Bank Sta=4497.6,4501.6
Exp/Cntr=0.3,0.1

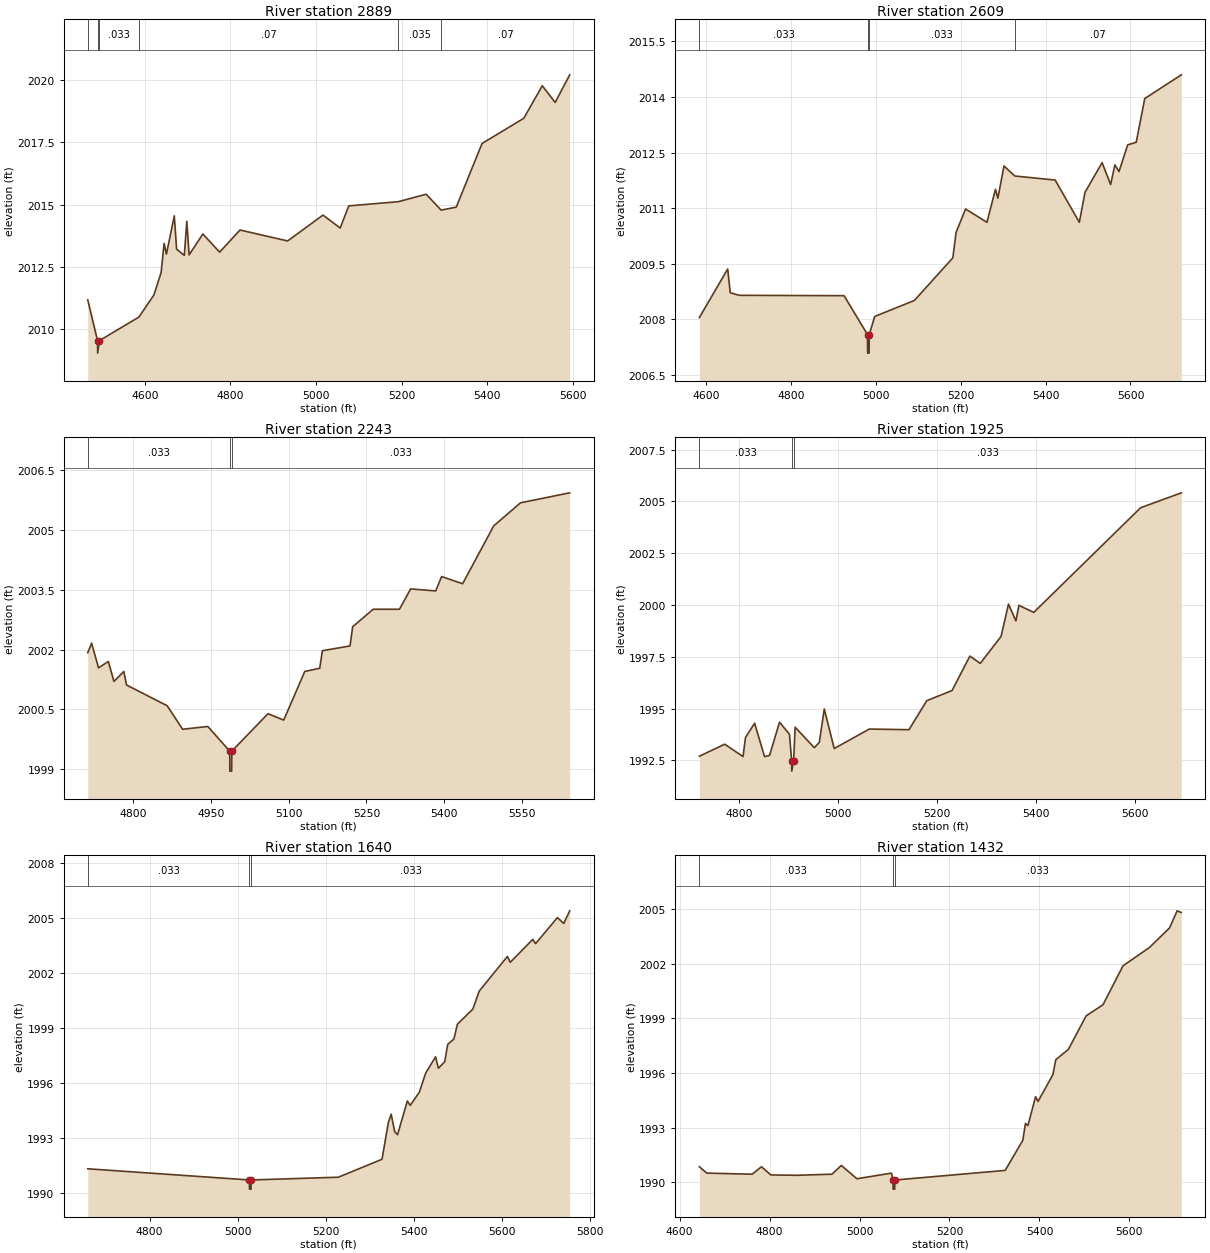
Type RM Length L Ch R = 1,2889,280,280,280
BEGIN DESCRIPTION:
Elm 89 4007
END DESCRIPTION:
XS GIS Cut Line= 3
      1535916.94      6770383.44      1536408.98      6770589.65
      1536998.85      6770532.90
#Sta/Elev= 30
  4466.5 2011.17  4489.4 2009.53  4489.6 2009.03  4493.4 2009.53  4586.0 2010.48
  4621.1 2011.37  4637.9 2012.27  4644.9 2013.44  4650.3 2013.01  4668.7 2014.55
  4674.1 2013.21  4692.1 2012.96  4697.9 2014.33  4703.3 2012.98  4735.5 2013.82
  4774.6 2013.09  4822.2 2013.98  4933.6 2013.54  5016.1 2014.58  5056.3 2014.06
  5076.4 2014.95  5192.4 2015.12  5257.2 2015.42  5292.2 2014.78  5327.5 2014.90
  5387.8 2017.46  5485.2 2018.47  5528.5 2019.78  5558.6 2019.11  5592.6 2020.22
#Mann=6,-1,0
  4466.5   0.033       0  4489.4    0.07       0  4493.4   0.033       0
  4586.0    0.07       0  5192.4   0.035       0  5292.2    0.07       0
Bank Sta=4489.4,4493.4
Exp/Cntr=0.3,0.1

Type RM Length L Ch R = 1,2609,366,366,366
BEGIN DESCRIPTION:
Elm 89 4006
END DESCRIPTION:
XS GIS Cut Line= 3
      1535906.54      6770584.83      1536254.71      6770812.88
      1536970.73      6770738.25
#Sta/Elev= 30
  4583.8 2008.05  4650.6 2009.36  4656.6 2008.72  4677.6 2008.65  4924.9 2008.64
  4980.2 2007.59  4980.4 2007.09  4983.9 2007.09  4984.2 2007.59  4997.2 2008.08
  5090.5 2008.51  5181.3 2009.66  5189.0 2010.35  5211.4 2010.98  5261.7 2010.62
  5281.8 2011.51  5287.5 2011.27  5301.9 2012.14  5327.3 2011.87  5422.6 2011.76
  5479.5 2010.62  5492.9 2011.43  5533.2 2012.23  5553.3 2011.64  5563.3 2012.17
  5573.0 2011.99  5593.5 2012.71  5613.6 2012.78  5633.7 2013.96  5719.9 2014.60
#Mann=4,-1,0
  4583.8   0.033       0  4980.2   0.033       0  4984.2   0.033       0
  5327.3    0.07       0
Bank Sta=4980.2,4984.2
Exp/Cntr=0.3,0.1

Type RM Length L Ch R = 1,2243,318,318,318
BEGIN DESCRIPTION:
Elm 89 4005
END DESCRIPTION:
XS GIS Cut Line= 3
      1535888.10      6771036.35      1536156.08      6771142.13
      1536788.49      6771027.55
#Sta/Elev= 30
  4711.9 2001.92  4719.3 2002.16  4732.7 2001.54  4751.6 2001.70  4762.5 2001.20
  4781.5 2001.45  4786.8 2001.11  4865.3 2000.59  4895.1 2000.00  4943.8 2000.07
  4986.1 1999.45  4986.3 1998.95  4989.8 1998.95  4990.1 1999.45  5059.9 2000.39
  5090.4 2000.23  5131.0 2001.45  5159.9 2001.53  5165.0 2001.97  5218.4 2002.09
  5223.5 2002.57  5263.1 2003.01  5313.9 2003.01  5335.5 2003.52  5383.9 2003.47
  5395.3 2003.83  5435.9 2003.65  5495.9 2005.10  5547.7 2005.68  5642.7 2005.93
#Mann=3,-1,0
  4711.9   0.033       0  4986.1   0.033       0  4990.1   0.033       0
Bank Sta=4986.1,4990.1
Exp/Cntr=0.3,0.1

Type RM Length L Ch R = 1,1925,285,285,285
BEGIN DESCRIPTION:
Elm 89 4004
END DESCRIPTION:
XS GIS Cut Line= 3
      1535923.94      6771471.99      1536202.73      6771443.94
      1536778.06      6771057.08
#Sta/Elev= 30
  4719.8 1992.70  4771.1 1993.28  4808.0 1992.68  4813.0 1993.61  4831.4 1994.29
  4851.5 1992.68  4861.6 1992.74  4881.7 1994.34  4901.8 1993.76  4906.2 1992.48
  4906.4 1991.98  4910.2 1992.48  4913.2 1994.10  4952.0 1993.11  4962.1 1993.37
  4972.1 1994.98  4992.2 1993.07  5063.0 1994.01  5143.2 1993.98  5179.2 1995.38
  5230.2 1995.87  5266.2 1997.53  5287.2 1997.18  5329.2 1998.48  5344.2 2000.04
  5359.2 1999.23  5365.2 1999.98  5395.2 1999.64  5611.1 2004.69  5693.3 2005.41
#Mann=3,-1,0
  4719.8   0.033       0  4906.2   0.033       0  4910.2   0.033       0
Bank Sta=4906.2,4910.2
Exp/Cntr=0.3,0.1

Type RM Length L Ch R = 1,1640,208,208,208
BEGIN DESCRIPTION:
Elm 89 4003
END DESCRIPTION:
XS GIS Cut Line= 3
      1536010.71      6771789.71      1536324.65      6771658.13
      1536798.77      6771072.88
#Sta/Elev= 30
  4659.6 1991.30  5026.4 1990.69  5026.6 1990.19  5030.1 1990.19  5030.4 1990.69
  5228.2 1990.84  5327.3 1991.82  5341.7 1993.83  5348.1 1994.28  5356.0 1993.33
  5362.5 1993.16  5384.8 1995.00  5391.2 1994.76  5412.0 1995.48  5426.4 1996.52
  5448.7 1997.41  5455.2 1996.79  5469.6 1997.14  5476.3 1998.09  5490.4 1998.38
  5498.3 1999.19  5533.5 2000.02  5547.9 2001.00  5611.8 2002.89  5618.3 2002.57
  5669.3 2003.82  5675.8 2003.59  5725.3 2005.01  5739.7 2004.69  5753.2 2005.38
#Mann=3,-1,0
  4659.6   0.033       0  5026.4   0.033       0  5030.4   0.033       0
Bank Sta=5026.4,5030.4
Exp/Cntr=0.3,0.1

Type RM Length L Ch R = 1,1432,314,314,314
BEGIN DESCRIPTION:
Elm 89 4002
END DESCRIPTION:
XS GIS Cut Line= 3
      1536283.32      6772020.57      1536507.30      6771743.86
      1536822.62      6771101.70
#Sta/Elev= 30
  4644.0 1990.85  4660.6 1990.50  4761.3 1990.44  4782.1 1990.85  4802.9 1990.40
  4860.4 1990.38  4938.7 1990.44  4959.6 1990.92  4994.2 1990.19  5071.0 1990.50
  5074.6 1990.12  5074.8 1989.62  5078.3 1989.62  5078.6 1990.12  5323.9 1990.65
  5363.0 1992.30  5368.9 1993.23  5374.4 1993.11  5391.4 1994.70  5396.9 1994.44
  5429.9 1995.91  5436.3 1996.73  5464.4 1997.30  5503.8 1999.14  5541.3 1999.75
  5585.8 2001.89  5644.3 2002.89  5689.2 2003.97  5706.1 2004.91  5715.4 2004.82
#Mann=3,-1,0
  4644.0   0.033       0  5074.6   0.033       0  5078.6   0.033       0
Bank Sta=5074.6,5078.6
Exp/Cntr=0.3,0.1

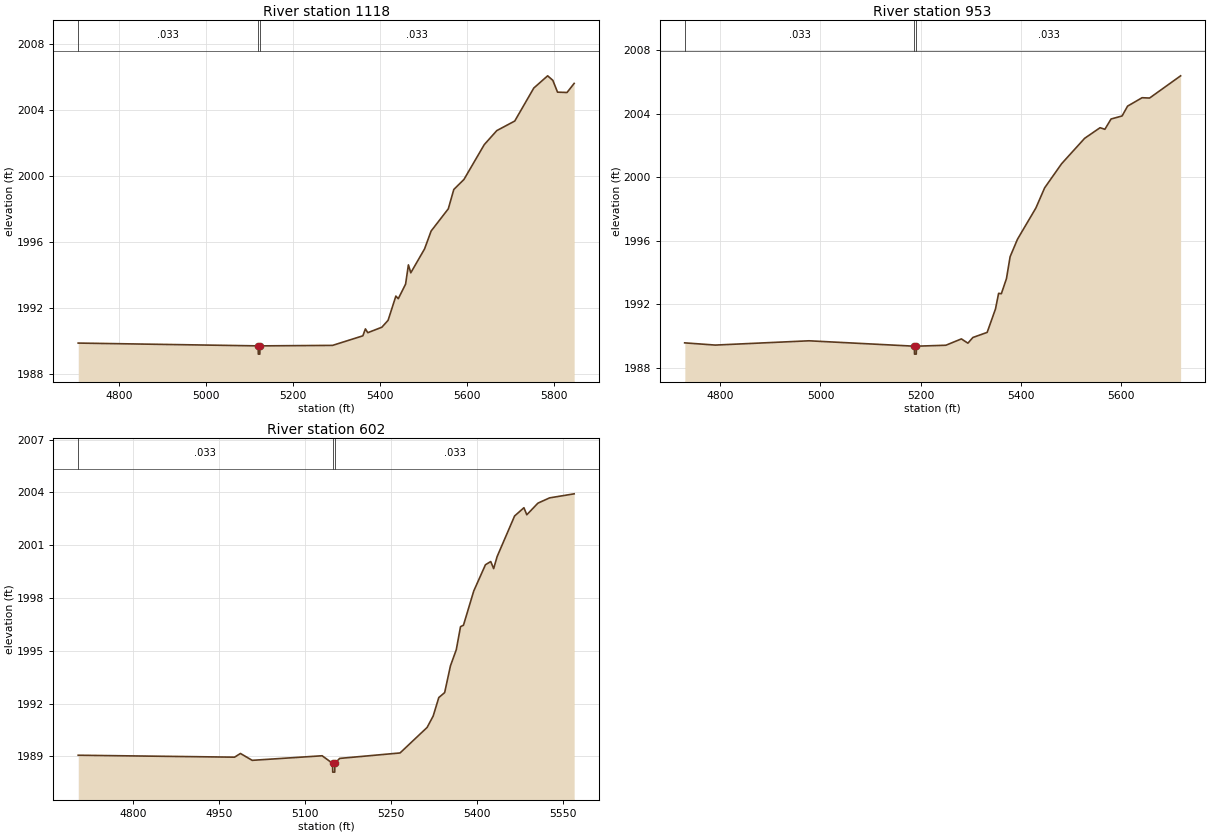
Type RM Length L Ch R = 1,1118,165,165,165
BEGIN DESCRIPTION:
Elm 89 4001
END DESCRIPTION:
XS GIS Cut Line= 3
      1536616.64      6772093.49      1536762.60      6771838.17
      1537102.73      6771063.01
#Sta/Elev= 30
  4705.9 1989.90  5119.9 1989.73  5120.1 1989.23  5123.6 1989.23  5123.9 1989.73
  5290.9 1989.76  5360.6 1990.34  5366.4 1990.76  5371.9 1990.53  5404.2 1990.86
  5418.6 1991.28  5436.5 1992.75  5442.0 1992.59  5458.8 1993.47  5465.3 1994.64
  5470.8 1994.16  5502.5 1995.61  5517.5 1996.69  5557.1 1998.04  5569.7 1999.21
  5593.1 1999.82  5639.8 2001.93  5668.6 2002.78  5709.9 2003.36  5753.7 2005.36
  5785.5 2006.10  5797.4 2005.83  5808.3 2005.11  5830.1 2005.09  5846.5 2005.64
#Mann=3,-1,0
  4705.9   0.033       0  5119.9   0.033       0  5123.9   0.033       0
Bank Sta=5119.9,5123.9
Exp/Cntr=0.3,0.1

Type RM Length L Ch R = 1,953,351,351,351
BEGIN DESCRIPTION:
Elm 89 3999
END DESCRIPTION:
XS GIS Cut Line= 3
      1536844.05      6772058.84      1536910.92      6771795.81
      1537211.53      6771141.67
#Sta/Elev= 30
  4728.6 1989.56  4789.8 1989.42  4977.1 1989.69  5187.8 1989.35  5188.0 1988.85
  5191.5 1988.85  5191.8 1989.35  5250.7 1989.41  5281.7 1989.81  5294.7 1989.54
  5304.7 1989.90  5333.2 1990.22  5349.8 1991.69  5356.1 1992.68  5361.6 1992.66
  5371.8 1993.61  5379.1 1994.99  5393.8 1996.09  5430.6 1998.06  5448.1 1999.33
  5482.0 2000.85  5528.0 2002.45  5558.9 2003.12  5568.5 2003.02  5580.9 2003.67
  5602.9 2003.86  5613.9 2004.48  5642.9 2005.01  5657.9 2004.99  5719.9 2006.39
#Mann=3,-1,0
  4728.6   0.033       0  5187.8   0.033       0  5191.8   0.033       0
Bank Sta=5187.8,5191.8
Exp/Cntr=0.3,0.1

Type RM Length L Ch R = 1,602,0,0,0
BEGIN DESCRIPTION:
Elm 89 3998
END DESCRIPTION:
XS GIS Cut Line= 3
      1537132.25      6772083.10      1537201.59      6771795.85
      1537305.86      6771235.87
#Sta/Elev= 30
  4704.5 1989.06  4977.2 1988.95  4987.5 1989.16  5008.0 1988.77  5130.0 1989.03
  5148.2 1988.60  5148.5 1988.10  5152.0 1988.10  5152.2 1988.60  5160.6 1988.88
  5265.9 1989.19  5313.1 1990.64  5323.7 1991.29  5333.5 1992.34  5343.7 1992.62
  5353.8 1994.14  5364.0 1995.06  5371.4 1996.37  5376.5 1996.45  5394.5 1998.40
  5414.9 1999.89  5424.1 2000.07  5429.2 1999.67  5435.2 2000.35  5465.7 2002.66
  5482.0 2003.13  5487.0 2002.73  5506.4 2003.39  5526.8 2003.69  5569.6 2003.92
#Mann=3,-1,0
  4704.5   0.033       0  5148.2   0.033       0  5152.2   0.033       0
Bank Sta=5148.2,5152.2
Exp/Cntr=0.3,0.1

Chan Stop Cuts=-1