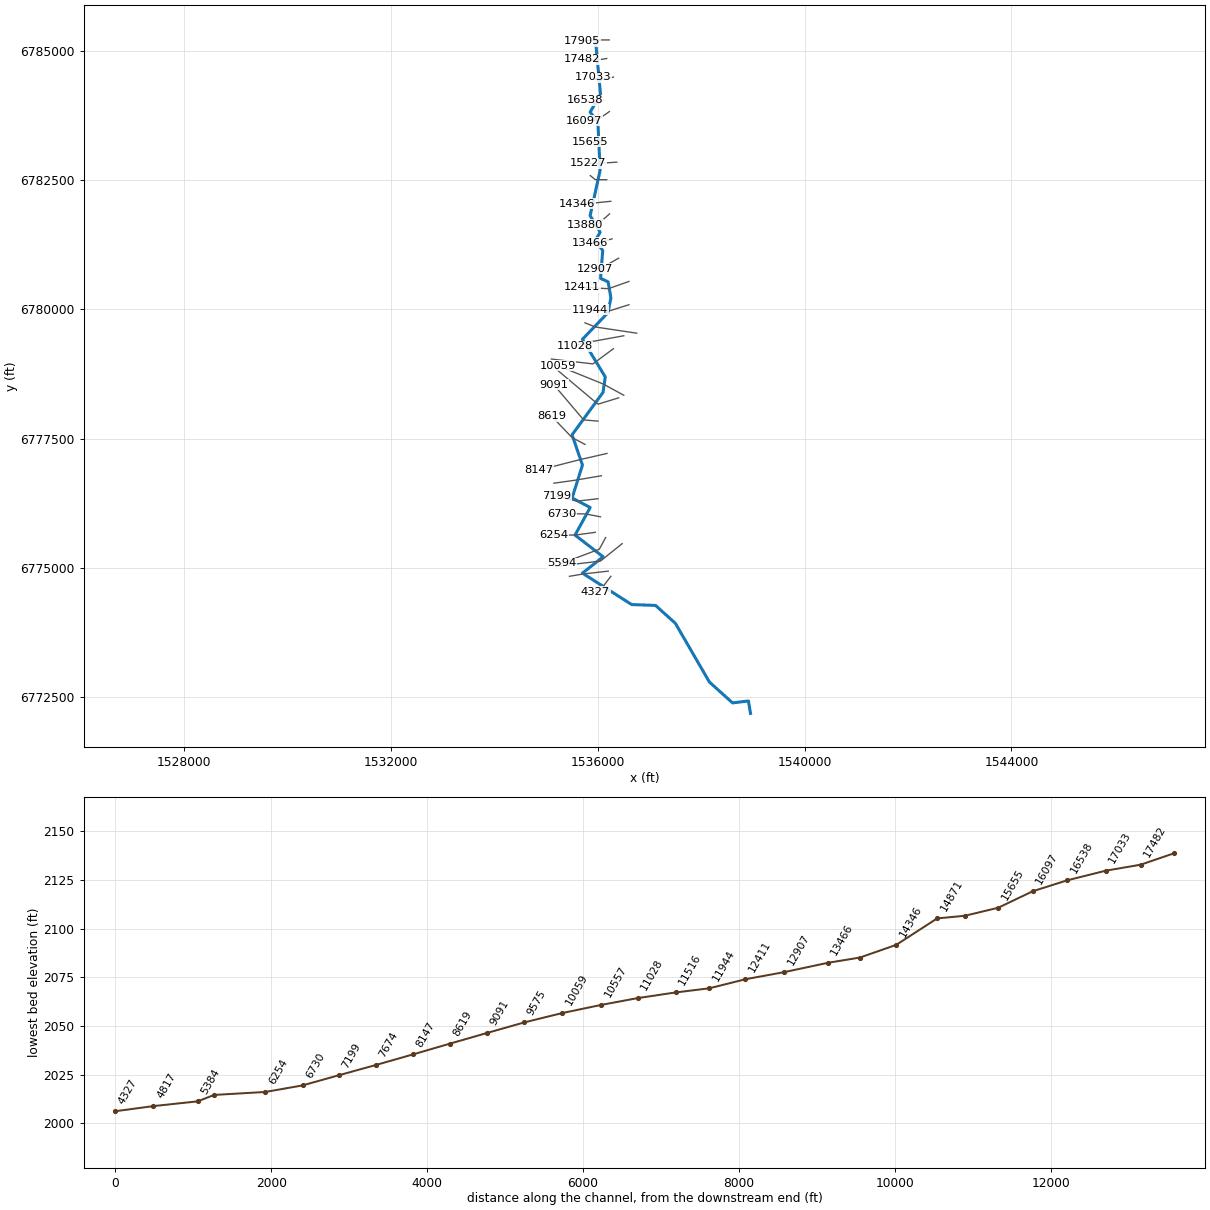
--- Elm 90.prj (project) ---

Proj Title=Elm 90 Base Level Engineering
Current Plan=p01
Default Exp/Contr=0.3,0.1
English Units
Geom File=g01
Flow File=f01
Plan File=p01
BEGIN DESCRIPTION:
Elm 90
END DESCRIPTION:

--- Elm 90.p01 (plan) ---

Plan Title=Multiple Run
Short Identifier=Multiple
Geom File=g01
Flow File=f01
Subcritical Flow
K Sum by GR= 0
Std Step Tol= 0.01
Critical Tol= 0.01
Num of Std Step Trials= 20
Max Error Tol= 0.3
Flow Tol Ratio= 0.001
Split Flow NTrial= 30
Split Flow Tol= 0.02
Split Flow Ratio= 0.02
Log Output Level= 0
Friction Slope Method= 1
Unsteady Friction Slope Method= 2
Unsteady Bridges Friction Slope Method= 1
Parabolic Critical Depth
Global Vel Dist=  1 , 1 , 1
Global Log Level= 0
CheckData=True
Encroach Param= -1, 0, 0, 0
BEGIN DESCRIPTION:
Multiple Run
END DESCRIPTION:

--- Elm 90.f01 (steady flow) ---

Flow Title=Multiple
Number of Profiles=7
Profile Names=10-year,25-year,50-year,1pct_min,100-year,1pct_plu,500-year
River Rch & RM= Elm 90,Reach-1,17905
     364     525     664     521     835    1150    1340
River Rch & RM= Elm 90,Reach-1,17033
     522     762     970     767    1230    1690    1990
River Rch & RM= Elm 90,Reach-1,7199
     569     830    1060     833    1340    1840    2160
Boundary for River Rch & Prof#=Elm 90,Reach-1,1
Up Type=0
Dn Type=3
Dn Slope=0.005
Boundary for River Rch & Prof#=Elm 90,Reach-1,2
Up Type=0
Dn Type=3
Dn Slope=0.005
Boundary for River Rch & Prof#=Elm 90,Reach-1,3
Up Type=0
Dn Type=3
Dn Slope=0.005
Boundary for River Rch & Prof#=Elm 90,Reach-1,4
Up Type=0
Dn Type=3
Dn Slope=0.005
Boundary for River Rch & Prof#=Elm 90,Reach-1,5
Up Type=0
Dn Type=3
Dn Slope=0.005
Boundary for River Rch & Prof#=Elm 90,Reach-1,6
Up Type=0
Dn Type=3
Dn Slope=0.005
Boundary for River Rch & Prof#=Elm 90,Reach-1,7
Up Type=0
Dn Type=3
Dn Slope=0.005

--- Elm 90.g01 (geometry) ---

Geom Title=Existing Conditions

River Reach=Elm 90,Reach-1
Reach XY= 30
      1535955.00      6785238.00      1536055.18      6784156.43
      1535854.43      6783810.80      1536003.95      6783627.57
      1536047.47      6782687.99      1535854.80      6781810.65
      1536047.12      6781491.22      1535954.19      6781324.29
      1536097.68      6781138.10      1536056.13      6780597.41
      1536201.89      6780530.32      1536255.42      6780219.67
      1536197.19      6779931.81      1535705.19      6779419.75
      1536147.21      6778691.42      1536102.91      6778393.26
      1535505.18      6777572.92      1535705.85      6776987.99
      1535505.88      6776352.70      1535855.52      6776167.96
      1535562.78      6775634.60      1536105.37      6775215.06
      1535705.69      6774898.69      1536656.55      6774291.75
      1537118.67      6774274.77      1537501.68      6773929.95
      1538160.59      6772793.61      1538606.64      6772391.14
      1538915.19      6772427.68      1538955.00      6772188.00

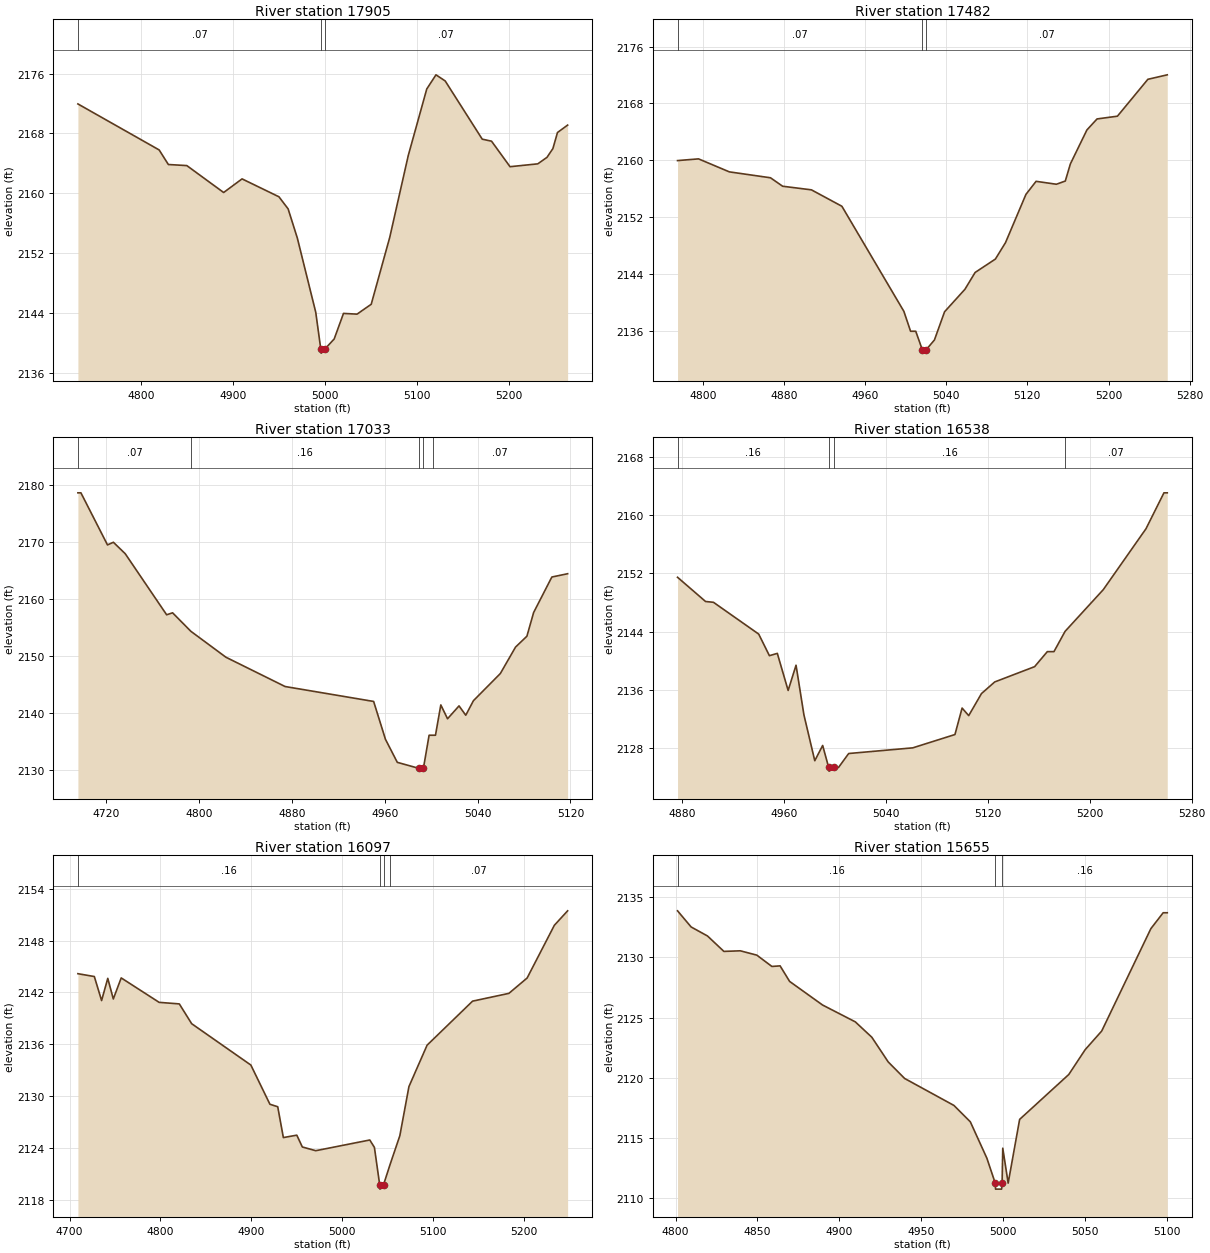
Type RM Length L Ch R = 1,17905,423,423,423
BEGIN DESCRIPTION:
162
END DESCRIPTION:
XS GIS Cut Line= 3
      1536223.18      6785207.04      1535954.88      6785206.20
      1535692.73      6785181.63
#Sta/Elev= 30
  4731.7 2171.95  4819.9 2165.80  4829.9 2163.85  4849.9 2163.71  4889.9 2160.11
  4909.9 2161.93  4949.9 2159.54  4959.9 2157.92  4969.9 2154.02  4989.9 2144.09
  4995.4 2139.14  4995.7 2138.64  4999.4 2139.14  5009.9 2140.53  5020.0 2143.95
  5034.7 2143.85  5050.1 2145.17  5070.2 2154.11  5090.3 2165.05  5110.4 2173.95
  5120.4 2175.84  5130.4 2175.02  5170.6 2167.24  5180.7 2166.97  5200.8 2163.56
  5230.9 2163.94  5240.9 2164.81  5247.3 2165.98  5252.3 2168.13  5263.3 2169.12
#Mann=3,-1,0
  4731.7    0.07       0  4995.4    0.07       0  4999.4    0.07       0
Bank Sta=4995.4,4999.4
Exp/Cntr=0.3,0.1

Type RM Length L Ch R = 1,17482,449,449,449
BEGIN DESCRIPTION:
809
END DESCRIPTION:
XS GIS Cut Line= 3
      1536175.51      6784848.17      1535946.83      6784813.24
      1535695.96      6784829.12
#Sta/Elev= 30
  4775.2 2159.95  4795.9 2160.19  4826.3 2158.36  4866.8 2157.53  4878.8 2156.34
  4907.2 2155.83  4937.2 2153.52  4998.3 2138.73  5004.9 2135.93  5010.0 2135.93
  5016.4 2133.35  5016.6 2132.85  5020.1 2132.85  5020.4 2133.35  5028.4 2134.70
  5038.4 2138.67  5058.5 2141.84  5068.5 2144.20  5088.5 2146.09  5098.5 2148.41
  5118.6 2155.19  5128.6 2157.03  5148.6 2156.62  5157.4 2157.07  5162.4 2159.48
  5178.7 2164.26  5188.7 2165.81  5208.8 2166.20  5238.8 2171.39  5257.9 2172.02
#Mann=3,-1,0
  4775.2    0.07       0  5016.4    0.07       0  5020.4    0.07       0
Bank Sta=5016.4,5020.4
Exp/Cntr=0.3,0.1

Type RM Length L Ch R = 1,17033,495,495,495
BEGIN DESCRIPTION:
161
END DESCRIPTION:
XS GIS Cut Line= 3
      1536305.01      6784488.00      1536006.41      6784428.36
      1535905.04      6784487.98
#Sta/Elev= 30
  4695.5 2178.60  4698.1 2178.60  4721.0 2169.46  4726.1 2169.92  4736.3 2167.91
  4772.0 2157.19  4777.1 2157.54  4792.9 2154.29  4823.1 2149.74  4874.1 2144.60
  4950.4 2141.98  4960.6 2135.33  4970.8 2131.29  4989.2 2130.25  4989.4 2129.75
  4993.3 2130.25  4998.2 2136.05  5001.4 2136.05  5003.7 2136.05  5008.3 2141.37
  5014.1 2138.94  5024.0 2141.20  5029.8 2139.56  5036.4 2142.11  5059.6 2146.88
  5072.7 2151.52  5082.5 2153.43  5088.3 2157.59  5104.0 2163.82  5117.6 2164.40
#Mann=5,-1,0
  4695.5    0.07       0  4792.9    0.16       0  4989.2    0.07       0
  4993.3    0.16       0  5001.4    0.07       0
Bank Sta=4989.2,4993.3
Exp/Cntr=0.3,0.1

Type RM Length L Ch R = 1,16538,441,441,441
BEGIN DESCRIPTION:
160
END DESCRIPTION:
XS GIS Cut Line= 3
      1536105.00      6784038.00      1536005.41      6783964.96
      1535755.05      6784037.99
#Sta/Elev= 30
  4876.5 2151.46  4898.5 2148.13  4904.7 2148.02  4940.2 2143.65  4948.6 2140.68
  4954.8 2141.00  4963.3 2135.90  4969.5 2139.37  4975.7 2132.53  4984.2 2126.24
  4990.4 2128.34  4995.1 2125.31  4995.4 2124.81  4999.3 2125.31  5002.8 2125.31
  5010.8 2127.23  5061.1 2128.01  5094.2 2129.84  5099.8 2133.48  5105.0 2132.44
  5115.0 2135.47  5125.4 2137.07  5156.7 2139.17  5166.7 2141.24  5171.9 2141.24
  5180.6 2144.02  5210.6 2149.76  5244.1 2158.13  5258.2 2163.07  5260.8 2163.07
#Mann=4,-1,0
  4876.5    0.16       0  4995.1    0.07       0  4999.3    0.16       0
  5180.6    0.07       0
Bank Sta=4995.1,4999.3
Exp/Cntr=0.3,0.1

Type RM Length L Ch R = 1,16097,442,442,442
BEGIN DESCRIPTION:
159
END DESCRIPTION:
XS GIS Cut Line= 3
      1536226.32      6783822.38      1535988.57      6783654.76
      1535740.43      6783641.35
#Sta/Elev= 30
  4709.1 2144.16  4727.2 2143.83  4735.2 2141.05  4742.0 2143.62  4748.1 2141.23
  4756.8 2143.67  4798.6 2140.84  4820.8 2140.66  4834.4 2138.37  4899.6 2133.58
  4920.6 2129.04  4929.2 2128.75  4935.4 2125.18  4950.2 2125.46  4956.3 2124.09
  4971.1 2123.66  5030.6 2124.90  5035.7 2124.04  5041.5 2119.71  5041.8 2119.21
  5045.7 2119.71  5053.1 2122.11  5063.7 2125.40  5073.7 2131.08  5093.7 2135.88
  5143.8 2140.98  5183.8 2141.88  5203.9 2143.66  5233.9 2149.77  5248.5 2151.44
#Mann=4,-1,0
  4709.1    0.16       0  5041.5    0.07       0  5045.7    0.16       0
  5053.1    0.07       0
Bank Sta=5041.5,5045.7
Exp/Cntr=0.3,0.1

Type RM Length L Ch R = 1,15655,428,428,428
BEGIN DESCRIPTION:
158
END DESCRIPTION:
XS GIS Cut Line= 3
      1536153.25      6783247.54      1535954.98      6783232.95
      1535855.01      6783238.00
#Sta/Elev= 30
  4801.2 2133.87  4809.5 2132.53  4819.5 2131.78  4829.5 2130.50  4839.5 2130.55
  4849.6 2130.19  4858.8 2129.25  4863.8 2129.30  4869.6 2128.01  4889.7 2126.05
  4909.7 2124.65  4919.8 2123.37  4929.8 2121.32  4939.8 2119.95  4969.9 2117.71
  4979.9 2116.35  4990.0 2113.33  4995.1 2111.26  4995.3 2110.76  4999.0 2110.76
  4999.3 2111.26  4999.7 2114.16  5003.0 2111.26  5010.0 2116.55  5040.0 2120.28
  5050.0 2122.34  5060.1 2123.89  5090.1 2132.39  5097.6 2133.71  5100.1 2133.71
#Mann=3,-1,0
  4801.2    0.16       0  4995.1    0.07       0  4999.3    0.16       0
Bank Sta=4995.1,4999.3
Exp/Cntr=0.3,0.1

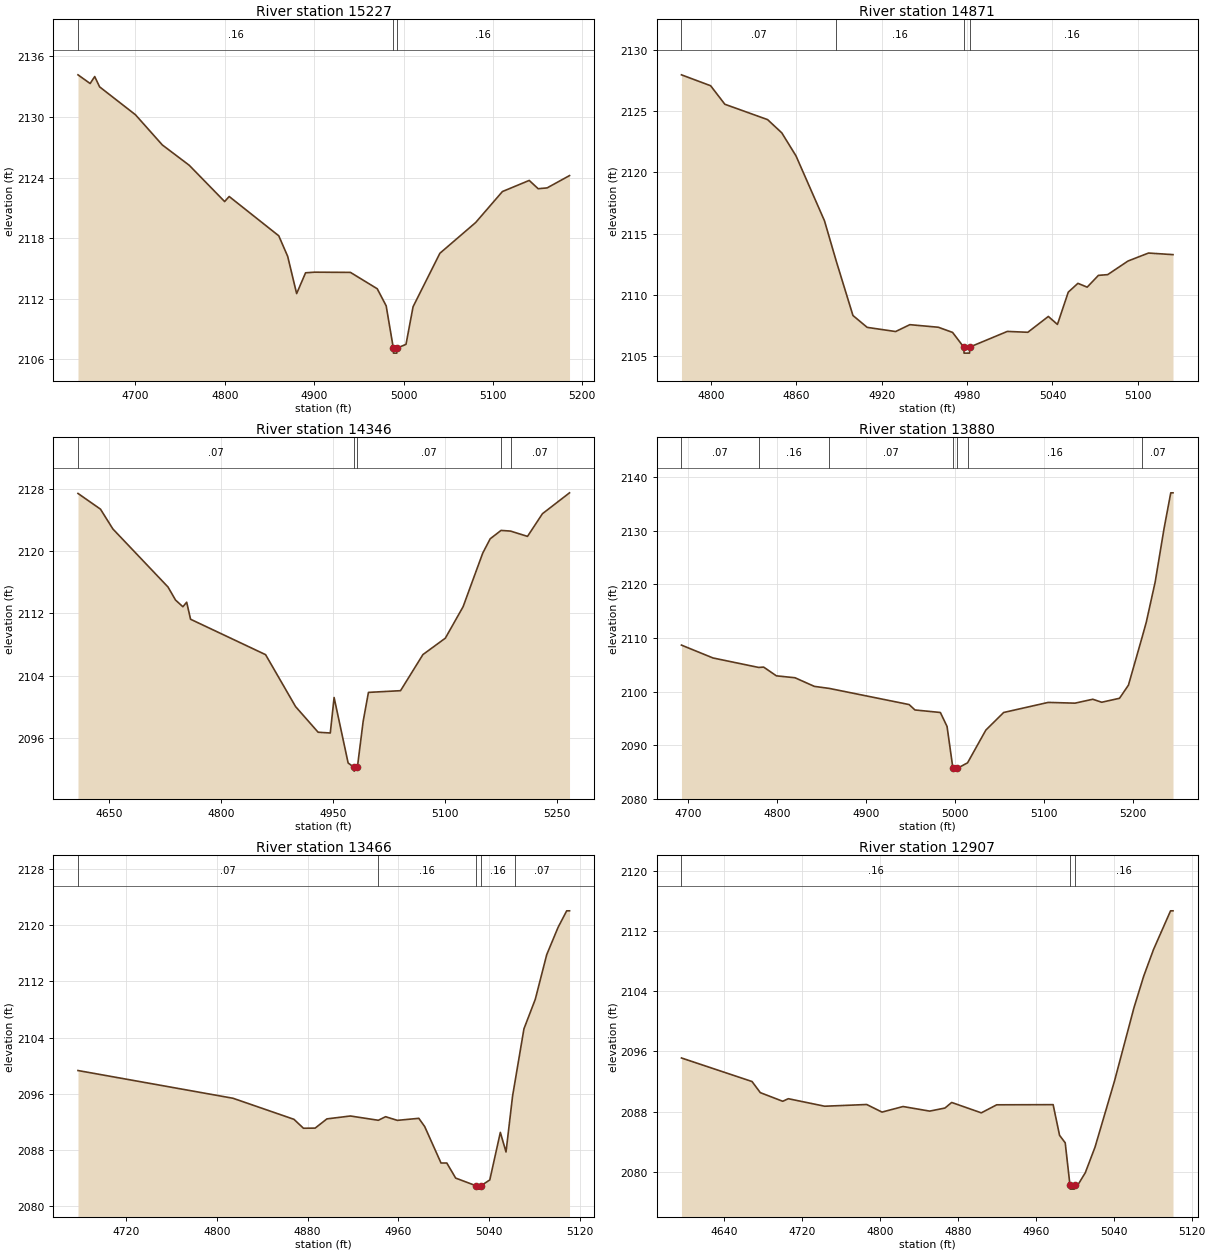
Type RM Length L Ch R = 1,15227,356,356,356
BEGIN DESCRIPTION:
157
END DESCRIPTION:
XS GIS Cut Line= 3
      1536369.18      6782844.20      1536005.68      6782820.02
      1535819.89      6782821.97
#Sta/Elev= 30
  4635.7 2134.17  4649.3 2133.31  4654.4 2134.00  4659.9 2132.98  4700.0 2130.22
  4730.1 2127.23  4760.2 2125.22  4799.8 2121.63  4804.9 2122.13  4860.4 2118.24
  4870.4 2116.20  4880.4 2112.52  4890.4 2114.58  4900.5 2114.64  4940.6 2114.62
  4970.6 2113.00  4980.6 2111.31  4988.6 2107.13  4988.8 2106.63  4992.5 2106.63
  4992.8 2107.13  5002.8 2107.50  5010.7 2111.22  5040.7 2116.51  5080.7 2119.55
  5110.7 2122.62  5140.7 2123.72  5150.7 2122.90  5160.7 2122.98  5185.8 2124.20
#Mann=3,-1,0
  4635.7    0.16       0  4988.6    0.07       0  4992.8    0.16       0
Bank Sta=4988.6,4992.8
Exp/Cntr=0.3,0.1

Type RM Length L Ch R = 1,14871,525,525,525
BEGIN DESCRIPTION:
156
END DESCRIPTION:
XS GIS Cut Line= 3
      1536175.51      6782504.39      1535954.82      6782506.43
      1535857.57      6782584.50
#Sta/Elev= 30
  4779.3 2127.96  4799.8 2127.07  4809.8 2125.56  4839.8 2124.31  4849.8 2123.23
  4859.8 2121.35  4879.8 2116.06  4888.0 2112.80  4899.8 2108.34  4909.8 2107.37
  4929.8 2107.03  4939.8 2107.59  4959.8 2107.38  4969.8 2106.96  4977.6 2105.77
  4977.9 2105.27  4981.7 2105.27  4982.0 2105.77  5008.3 2107.04  5022.7 2106.97
  5037.1 2108.26  5043.5 2107.61  5051.1 2110.24  5057.9 2110.96  5064.4 2110.65
  5072.3 2111.61  5078.8 2111.67  5093.1 2112.78  5107.5 2113.43  5124.7 2113.30
#Mann=4,-1,0
  4779.3    0.07       0  4888.0    0.16       0  4977.6    0.07       0
  4982.0    0.16       0
Bank Sta=4977.6,4982
Exp/Cntr=0.3,0.1

Type RM Length L Ch R = 1,14346,466,466,466
BEGIN DESCRIPTION:
155
END DESCRIPTION:
XS GIS Cut Line= 3
      1536254.96      6782088.00      1535865.85      6782047.65
      1535598.74      6782037.58
#Sta/Elev= 30
  4608.8 2127.46  4638.9 2125.44  4655.6 2122.88  4729.4 2115.41  4739.5 2113.73
  4749.3 2112.87  4754.4 2113.45  4759.6 2111.26  4860.1 2106.70  4900.3 2100.01
  4930.5 2096.71  4946.8 2096.61  4951.9 2101.18  4970.7 2092.75  4978.4 2092.20
  4978.7 2091.70  4983.1 2092.20  4990.8 2098.09  4997.9 2101.84  5040.9 2102.06
  5070.9 2106.71  5100.9 2108.82  5124.7 2112.87  5151.0 2119.77  5161.0 2121.62
  5175.6 2122.70  5188.4 2122.61  5211.0 2121.93  5231.0 2124.85  5267.3 2127.54
#Mann=5,-1,0
  4608.8    0.07       0  4978.4    0.07       0  4983.1    0.07       0
  5175.6    0.16       0  5188.4    0.07       0
Bank Sta=4978.4,4983.1
Exp/Cntr=0.3,0.1

Type RM Length L Ch R = 1,13880,414,414,414
BEGIN DESCRIPTION:
154
END DESCRIPTION:
XS GIS Cut Line= 3
      1536229.46      6781843.79      1535999.48      6781640.43
      1535754.99      6781638.00
#Sta/Elev= 30
  4693.0 2108.69  4728.4 2106.29  4779.7 2104.52  4785.2 2104.59  4799.5 2102.96
  4820.4 2102.60  4842.1 2100.99  4858.9 2100.61  4948.4 2097.60  4955.0 2096.59
  4983.5 2096.12  4991.0 2093.51  4997.6 2085.68  4998.0 2085.18  5002.3 2085.68
  5014.0 2086.73  5034.5 2092.83  5054.5 2096.12  5104.5 2098.00  5134.5 2097.86
  5154.5 2098.59  5164.5 2098.03  5184.5 2098.77  5194.5 2101.22  5210.0 2110.25
  5214.5 2112.95  5224.5 2120.46  5234.5 2130.47  5242.0 2137.10  5244.5 2137.10
#Mann=7,-1,0
  4693.0    0.07       0  4779.7    0.16       0  4858.9    0.07       0
  4997.6    0.07       0  5002.3    0.07       0  5014.0    0.16       0
  5210.0    0.07       0
Bank Sta=4997.6,5002.3
Exp/Cntr=0.3,0.1

Type RM Length L Ch R = 1,13466,559,559,559
BEGIN DESCRIPTION:
153
END DESCRIPTION:
XS GIS Cut Line= 3
      1536277.11      6781361.07      1535965.43      6781278.21
      1535854.97      6781288.00
#Sta/Elev= 30
  4677.5 2099.31  4814.2 2095.37  4867.9 2092.38  4876.3 2091.11  4886.6 2091.13
  4897.0 2092.44  4917.7 2092.85  4942.3 2092.24  4948.7 2092.75  4959.1 2092.23
  4978.0 2092.52  4983.2 2091.35  4997.6 2086.17  5002.7 2086.17  5010.5 2084.03
  5028.1 2082.96  5028.5 2082.46  5032.7 2082.46  5033.0 2082.96  5040.6 2083.77
  5049.9 2090.52  5054.9 2087.74  5060.7 2095.70  5062.4 2097.32  5070.7 2105.23
  5080.7 2109.43  5090.8 2115.78  5100.8 2119.65  5108.4 2122.00  5110.9 2122.00
#Mann=5,-1,0
  4677.5    0.07       0  4942.3    0.16       0  5028.1    0.07       0
  5033.0    0.16       0  5062.4    0.07       0
Bank Sta=5028.1,5033
Exp/Cntr=0.3,0.1

Type RM Length L Ch R = 1,12907,496,496,496
BEGIN DESCRIPTION:
152
END DESCRIPTION:
XS GIS Cut Line= 3
      1536404.98      6780987.99      1536055.75      6780785.66
      1535954.98      6780788.00
#Sta/Elev= 30
  4596.4 2095.13  4668.8 2092.00  4677.3 2090.52  4700.3 2089.37  4706.1 2089.71
  4743.4 2088.71  4786.5 2088.94  4802.2 2087.93  4823.8 2088.67  4851.1 2088.06
  4866.8 2088.47  4873.7 2089.21  4904.1 2087.83  4919.9 2088.90  4977.8 2088.92
  4984.4 2084.84  4990.2 2083.84  4995.1 2078.18  4995.4 2077.68  4999.6 2077.68
  5000.0 2078.18  5002.9 2078.18  5010.8 2079.86  5020.8 2083.27  5040.8 2092.08
  5060.8 2101.84  5070.8 2106.04  5080.8 2109.56  5098.3 2114.71  5100.8 2114.71
#Mann=3,-1,0
  4596.4    0.16       0  4995.1    0.07       0  5000.0    0.16       0
Bank Sta=4995.1,5000
Exp/Cntr=0.3,0.1

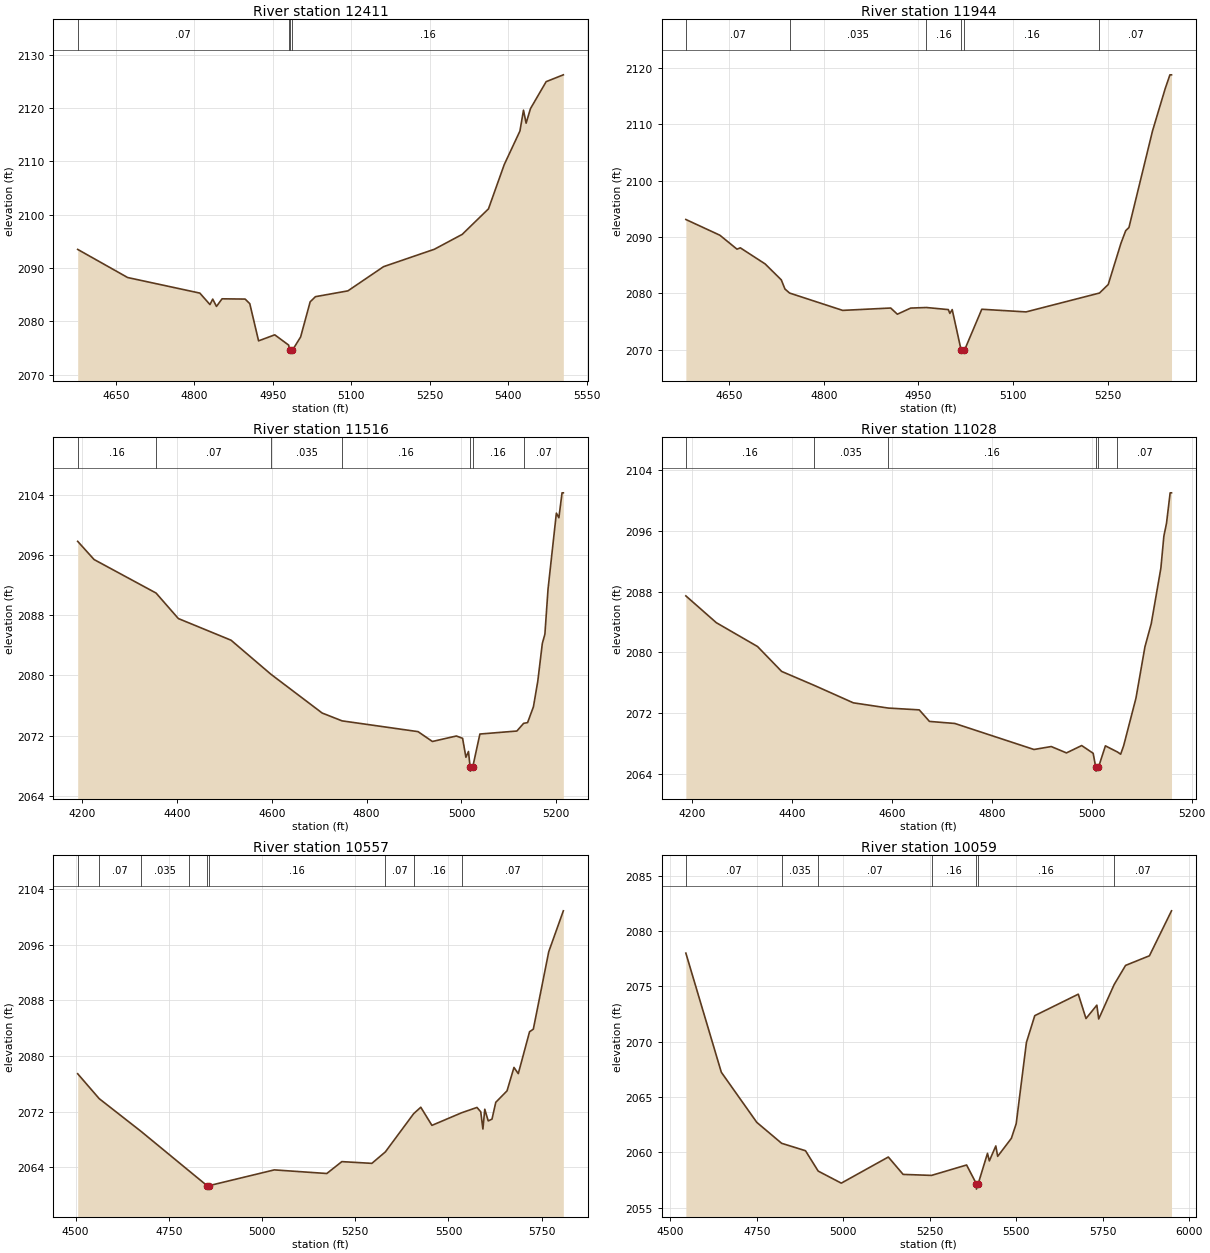
Type RM Length L Ch R = 1,12411,467,467,467
BEGIN DESCRIPTION:
151
END DESCRIPTION:
XS GIS Cut Line= 3
      1536605.02      6780538.01      1536206.40      6780397.68
      1535702.27      6780427.37
#Sta/Elev= 30
  4577.4 2093.49  4672.8 2088.22  4810.7 2085.30  4830.0 2083.15  4835.3 2084.17
  4842.5 2082.80  4853.1 2084.23  4897.2 2084.18  4906.1 2083.32  4922.9 2076.35
  4953.8 2077.48  4980.4 2075.55  4982.3 2074.55  4982.7 2074.05  4987.2 2074.55
  5003.2 2077.08  5021.4 2083.66  5031.5 2084.63  5093.5 2085.72  5161.7 2090.26
  5258.7 2093.52  5311.9 2096.31  5362.0 2101.09  5392.1 2109.38  5422.1 2115.68
  5428.9 2119.58  5433.9 2117.15  5442.2 2119.87  5472.2 2124.93  5505.0 2126.21
#Mann=4,-1,0
  4577.4    0.07       0  4980.4    0.16       0  4982.3    0.07       0
  4987.2    0.16       0
Bank Sta=4982.3,4987.2
Exp/Cntr=0.3,0.1

Type RM Length L Ch R = 1,11944,428,428,428
BEGIN DESCRIPTION:
150
END DESCRIPTION:
XS GIS Cut Line= 3
      1536604.97      6780087.99      1536205.29      6779962.88
      1535854.99      6779988.00
#Sta/Elev= 30
  4581.2 2093.10  4635.1 2090.31  4662.3 2087.83  4667.5 2088.07  4706.9 2085.21
  4732.5 2082.38  4738.3 2080.76  4745.6 2080.04  4829.8 2076.96  4906.0 2077.38
  4916.5 2076.28  4937.7 2077.37  4962.6 2077.47  4997.3 2077.10  4999.8 2076.43
  5003.5 2077.10  5017.7 2069.87  5018.1 2069.37  5022.9 2069.87  5050.4 2077.16
  5120.6 2076.69  5237.0 2080.04  5250.9 2081.56  5271.0 2088.86  5278.6 2091.12
  5283.7 2091.67  5321.1 2108.83  5341.2 2116.34  5348.7 2118.79  5351.2 2118.79
#Mann=6,-1,0
  4581.2    0.07       0  4745.6   0.035       0  4962.6    0.16       0
  5017.7    0.07       0  5022.9    0.16       0  5237.0    0.07       0
Bank Sta=5017.7,5022.9
Exp/Cntr=0.3,0.1

Type RM Length L Ch R = 1,11516,488,488,488
BEGIN DESCRIPTION:
149
END DESCRIPTION:
XS GIS Cut Line= 3
      1536754.99      6779538.00      1535954.40      6779657.76
      1535755.03      6779737.99
#Sta/Elev= 30
  4190.5 2097.81  4225.1 2095.39  4355.8 2090.94  4402.8 2087.55  4514.0 2084.67
  4598.2 2080.14  4706.2 2074.99  4748.2 2073.95  4908.4 2072.52  4938.7 2071.21
  4989.3 2071.94  5002.4 2071.63  5009.4 2069.11  5014.8 2069.88  5018.3 2067.77
  5018.7 2067.27  5023.6 2067.77  5038.9 2072.20  5116.9 2072.60  5131.1 2073.62
  5139.5 2073.72  5151.8 2075.82  5161.0 2079.22  5170.6 2084.25  5176.0 2085.47
  5182.6 2091.45  5200.2 2101.56  5205.5 2100.95  5212.2 2104.26  5214.9 2104.26
#Mann=7,-1,0
  4190.5    0.16       0  4355.8    0.07       0  4598.2   0.035       0
  4748.2    0.16       0  5018.3    0.07       0  5023.6    0.16       0
  5131.1    0.07       0
Bank Sta=5018.3,5023.6
Exp/Cntr=0.3,0.1

Type RM Length L Ch R = 1,11028,471,471,471
BEGIN DESCRIPTION:
148
END DESCRIPTION:
XS GIS Cut Line= 3
      1536504.98      6779488.00      1535704.91      6779342.44
      1535554.99      6779288.00
#Sta/Elev= 30
  4186.8 2087.45  4247.8 2083.92  4330.3 2080.78  4378.6 2077.50  4443.9 2075.66
  4522.2 2073.36  4592.2 2072.67  4654.3 2072.43  4674.7 2070.91  4725.5 2070.64
  4884.1 2067.21  4918.6 2067.60  4949.1 2066.76  4979.6 2067.73  5002.6 2066.71
  5007.8 2064.86  5008.3 2064.36  5013.2 2064.86  5027.1 2067.69  5051.3 2066.88
  5057.7 2066.59  5063.7 2067.72  5088.3 2073.97  5106.3 2080.74  5118.9 2083.78
  5138.2 2091.10  5144.2 2095.32  5149.5 2097.02  5156.8 2101.03  5159.5 2101.03
#Mann=6,-1,0
  4186.8    0.16       0  4443.9   0.035       0  4592.2    0.16       0
  5007.8    0.07       0  5013.2    0.16       0  5051.3    0.07       0
Bank Sta=5007.8,5013.2
Exp/Cntr=0.3,0.1

Type RM Length L Ch R = 1,10557,498,498,498
BEGIN DESCRIPTION:
147
END DESCRIPTION:
XS GIS Cut Line= 3
      1536305.04      6779238.03      1535907.53      6778944.05
      1535105.01      6779038.00
#Sta/Elev= 30
  4505.6 2077.45  4563.2 2073.87  4676.1 2069.13  4804.4 2063.46  4852.5 2061.34
  4852.9 2060.84  4858.0 2061.34  5032.8 2063.61  5173.7 2063.09  5214.0 2064.80
  5294.5 2064.55  5330.7 2066.20  5406.7 2071.71  5425.7 2072.63  5455.6 2070.02
  5535.5 2071.84  5576.4 2072.60  5586.5 2071.97  5592.3 2069.50  5597.3 2072.34
  5606.6 2070.66  5616.7 2070.92  5626.8 2073.34  5657.0 2074.99  5675.6 2078.36
  5687.2 2077.47  5717.4 2083.50  5727.5 2083.87  5768.9 2095.03  5808.0 2100.91
#Mann=9,-1,0
  4505.6    0.16       0  4563.2    0.07       0  4676.1   0.035       0
  4804.4    0.16       0  4852.5    0.07       0  4858.0    0.16       0
  5330.7    0.07       0  5406.7    0.16       0  5535.5    0.07       0
Bank Sta=4852.5,4858
Exp/Cntr=0.3,0.1

Type RM Length L Ch R = 1,10059,484,484,484
BEGIN DESCRIPTION:
146
END DESCRIPTION:
XS GIS Cut Line= 3
      1536505.01      6778338.00      1536105.72      6778555.95
      1535225.91      6778912.48
#Sta/Elev= 30
  4545.1 2077.99  4647.6 2067.23  4750.2 2062.70  4822.0 2060.81  4891.0 2060.14
  4927.7 2058.30  4994.5 2057.21  5130.5 2059.57  5173.3 2058.00  5255.4 2057.91
  5356.8 2058.85  5384.8 2057.17  5385.3 2056.67  5390.5 2057.17  5417.2 2059.90
  5422.6 2059.22  5441.3 2060.57  5446.7 2059.63  5486.3 2061.26  5500.3 2062.59
  5529.8 2069.92  5553.9 2072.34  5679.8 2074.28  5702.1 2072.08  5733.4 2073.29
  5738.8 2072.04  5783.5 2075.15  5816.5 2076.88  5885.5 2077.75  5949.3 2081.81
#Mann=7,-1,0
  4545.1    0.07       0  4822.0   0.035       0  4927.7    0.07       0
  5255.4    0.16       0  5384.8    0.07       0  5390.5    0.16       0
  5783.5    0.07       0
Bank Sta=5384.8,5390.5
Exp/Cntr=0.3,0.1

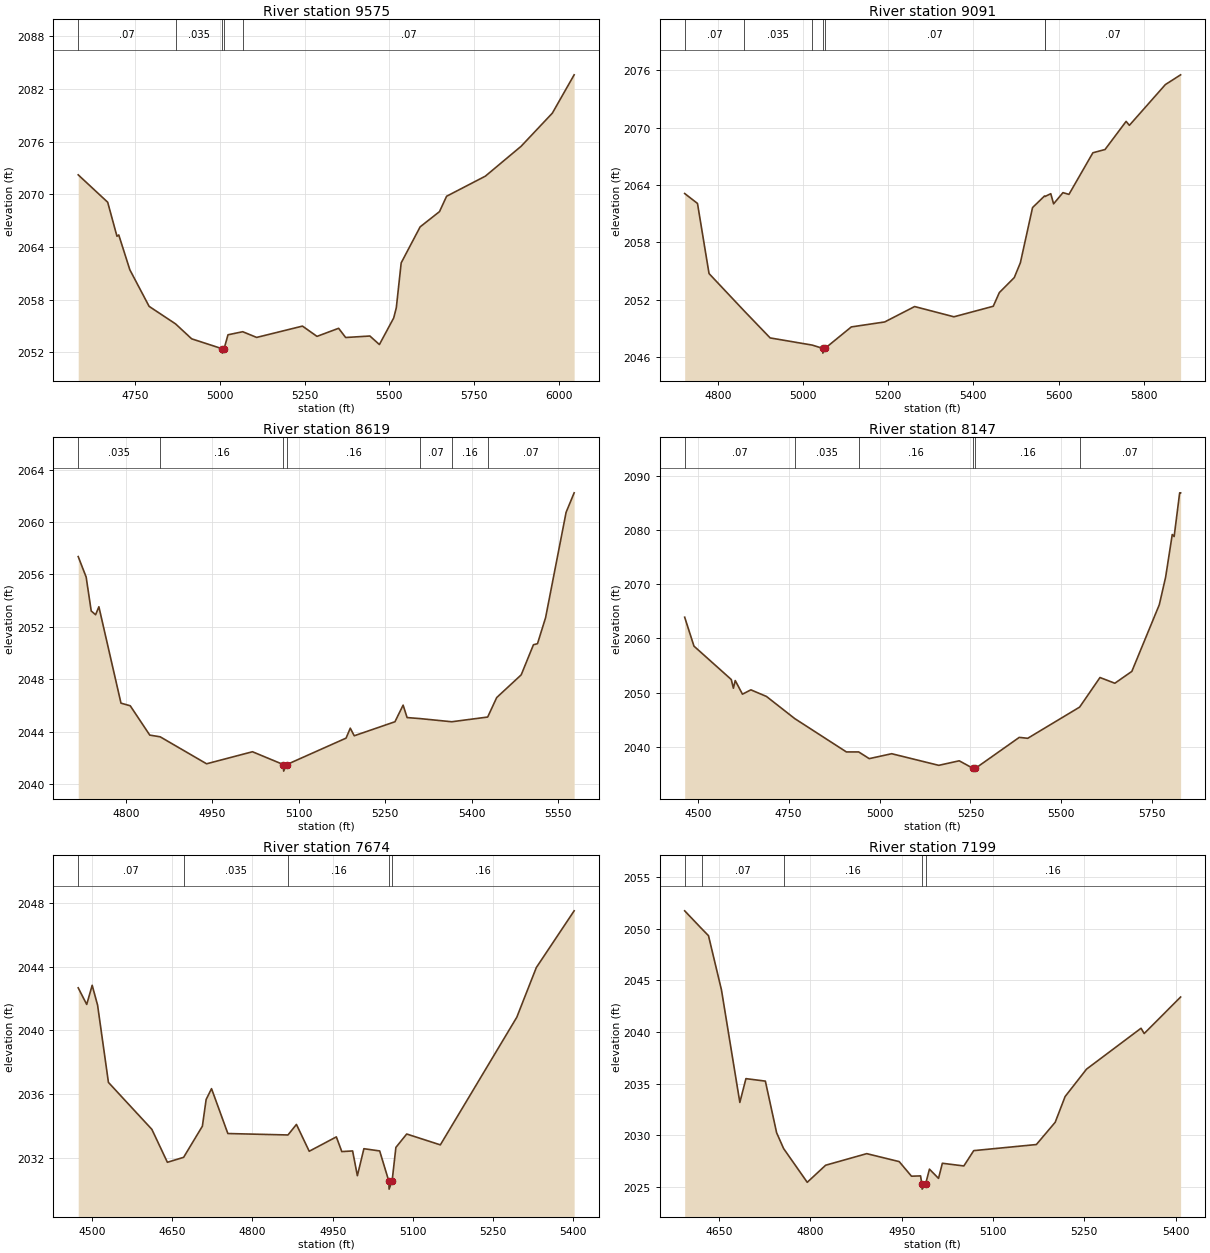
Type RM Length L Ch R = 1,9575,484,484,484
BEGIN DESCRIPTION:
145
END DESCRIPTION:
XS GIS Cut Line= 3
      1536405.05      6778288.01      1536005.65      6778165.04
      1535205.00      6778838.00
#Sta/Elev= 30
  4582.1 2072.22  4669.1 2069.10  4696.5 2065.22  4701.8 2065.37  4734.5 2061.40
  4791.4 2057.23  4869.5 2055.23  4917.0 2053.53  5007.0 2052.40  5007.5 2051.90
  5012.7 2052.40  5024.2 2053.99  5067.7 2054.34  5108.8 2053.69  5244.0 2054.98
  5286.9 2053.81  5350.7 2054.73  5371.5 2053.68  5443.0 2053.85  5471.1 2052.88
  5513.3 2055.91  5521.0 2057.07  5535.4 2062.19  5591.3 2066.29  5648.5 2068.03
  5669.4 2069.78  5783.8 2072.07  5889.2 2075.47  5981.5 2079.25  6045.9 2083.62
#Mann=5,-1,0
  4582.1    0.07       0  4869.5   0.035       0  5007.0   0.035       0
  5012.7   0.035       0  5067.7    0.07       0
Bank Sta=5007,5012.7
Exp/Cntr=0.3,0.1

Type RM Length L Ch R = 1,9091,472,472,472
BEGIN DESCRIPTION:
144
END DESCRIPTION:
XS GIS Cut Line= 3
      1536005.02      6777838.00      1535728.11      6777861.47
      1535154.97      6778538.03
#Sta/Elev= 30
  4722.1 2063.10  4752.2 2062.06  4779.3 2054.73  4861.5 2050.84  4922.8 2048.00
  5021.6 2047.25  5046.1 2046.91  5046.6 2046.41  5051.8 2046.91  5113.4 2049.15
  5191.8 2049.67  5262.1 2051.28  5354.4 2050.21  5446.7 2051.31  5461.0 2052.74
  5496.1 2054.31  5510.4 2055.86  5539.0 2061.63  5567.1 2062.84  5568.4 2062.79
  5581.8 2063.08  5588.4 2062.02  5610.4 2063.19  5624.5 2063.01  5680.7 2067.36
  5709.2 2067.70  5758.7 2070.64  5766.4 2070.23  5850.9 2074.49  5886.7 2075.51
#Mann=7,-1,0
  4722.1    0.07       0  4861.5   0.035       0  5021.6    0.07       0
  5046.1   0.035       0  5051.8    0.07       0  5567.1    0.16       0
  5568.4    0.07       0
Bank Sta=5046.1,5051.8
Exp/Cntr=0.3,0.1

Type RM Length L Ch R = 1,8619,472,472,472
BEGIN DESCRIPTION:
143
END DESCRIPTION:
XS GIS Cut Line= 3
      1535755.00      6777388.00      1535504.33      6777519.78
      1535104.97      6777938.04
#Sta/Elev= 30
  4716.8 2057.36  4730.6 2055.80  4739.4 2053.21  4747.0 2052.92  4752.7 2053.53
  4791.1 2046.17  4807.2 2045.97  4841.1 2043.73  4859.2 2043.60  4939.8 2041.54
  5019.5 2042.46  5073.2 2041.48  5073.7 2040.98  5079.0 2041.48  5182.1 2043.50
  5189.4 2044.26  5196.3 2043.68  5267.0 2044.75  5281.2 2046.02  5288.1 2045.07
  5310.9 2044.99  5365.7 2044.75  5428.1 2045.11  5443.8 2046.60  5486.3 2048.33
  5507.6 2050.63  5514.6 2050.71  5528.7 2052.70  5564.3 2060.74  5578.3 2062.23
#Mann=7,-1,0
  4716.8   0.035       0  4859.2    0.16       0  5073.2    0.07       0
  5079.0    0.16       0  5310.9    0.07       0  5365.7    0.16       0
  5428.1    0.07       0
Bank Sta=5073.2,5079
Exp/Cntr=0.3,0.1

Type RM Length L Ch R = 1,8147,473,473,473
BEGIN DESCRIPTION:
142
END DESCRIPTION:
XS GIS Cut Line= 3
      1536180.00      6777213.00      1535657.47      6777093.57
      1534854.98      6776888.00
#Sta/Elev= 30
  4464.0 2063.93  4489.6 2058.58  4592.2 2052.41  4598.0 2050.80  4603.1 2052.22
  4623.0 2049.70  4646.1 2050.50  4689.0 2049.28  4766.9 2045.18  4908.9 2039.02
  4942.7 2039.02  4971.8 2037.78  5033.5 2038.69  5163.0 2036.54  5219.3 2037.38
  5257.7 2035.97  5258.2 2035.47  5263.5 2035.97  5384.5 2041.71  5407.8 2041.54
  5550.6 2047.31  5606.6 2052.78  5647.4 2051.72  5694.2 2053.91  5769.8 2066.25
  5787.1 2071.32  5805.4 2079.22  5810.6 2078.85  5825.8 2086.93  5828.4 2086.93
#Mann=6,-1,0
  4464.0    0.07       0  4766.9   0.035       0  4942.7    0.16       0
  5257.7    0.07       0  5263.5    0.16       0  5550.6    0.07       0
Bank Sta=5257.7,5263.5
Exp/Cntr=0.3,0.1

Type RM Length L Ch R = 1,7674,475,475,475
BEGIN DESCRIPTION:
141
END DESCRIPTION:
XS GIS Cut Line= 3
      1536070.72      6776781.49      1535552.53      6776693.57
      1535154.99      6776638.00
#Sta/Elev= 30
  4474.4 2042.67  4490.3 2041.63  4500.5 2042.83  4510.6 2041.59  4530.9 2036.75
  4612.1 2033.81  4641.1 2031.75  4671.4 2032.06  4706.5 2034.01  4713.5 2035.68
  4723.6 2036.36  4754.1 2033.55  4866.5 2033.46  4882.3 2034.12  4906.2 2032.44
  4956.9 2033.34  4967.1 2032.42  4987.3 2032.46  4996.2 2030.91  5008.4 2032.60
  5037.9 2032.46  5055.0 2030.57  5055.5 2030.07  5061.1 2030.57  5068.2 2032.68
  5088.4 2033.52  5151.3 2032.84  5294.2 2040.83  5330.7 2043.94  5401.4 2047.49
#Mann=5,-1,0
  4474.4    0.07       0  4671.4   0.035       0  4866.5    0.16       0
  5055.0    0.07       0  5061.1    0.16       0
Bank Sta=5055,5061.1
Exp/Cntr=0.3,0.1

Type RM Length L Ch R = 1,7199,469,469,469
BEGIN DESCRIPTION:
140
END DESCRIPTION:
XS GIS Cut Line= 3
      1536004.95      6776337.99      1535601.30      6776290.77
      1535204.96      6776388.01
#Sta/Elev= 30
  4593.6 2051.71  4621.4 2049.99  4632.7 2049.31  4654.0 2044.07  4684.2 2033.19
  4694.2 2035.49  4726.1 2035.25  4744.6 2030.26  4756.1 2028.73  4794.9 2025.47
  4825.1 2027.12  4892.6 2028.24  4945.9 2027.47  4966.1 2026.06  4981.0 2026.09
  4983.1 2025.31  4983.6 2024.81  4989.3 2025.31  4995.6 2026.74  5010.5 2025.85
  5016.8 2027.31  5052.1 2027.05  5068.3 2028.53  5171.2 2029.12  5202.1 2031.27
  5218.4 2033.76  5253.6 2036.41  5343.1 2040.36  5348.3 2039.85  5408.1 2043.38
#Mann=5,-1,0
  4593.6    0.16       0  4621.4    0.07       0  4756.1    0.16       0
  4983.1    0.07       0  4989.3    0.16       0
Bank Sta=4983.1,4989.3
Exp/Cntr=0.3,0.1

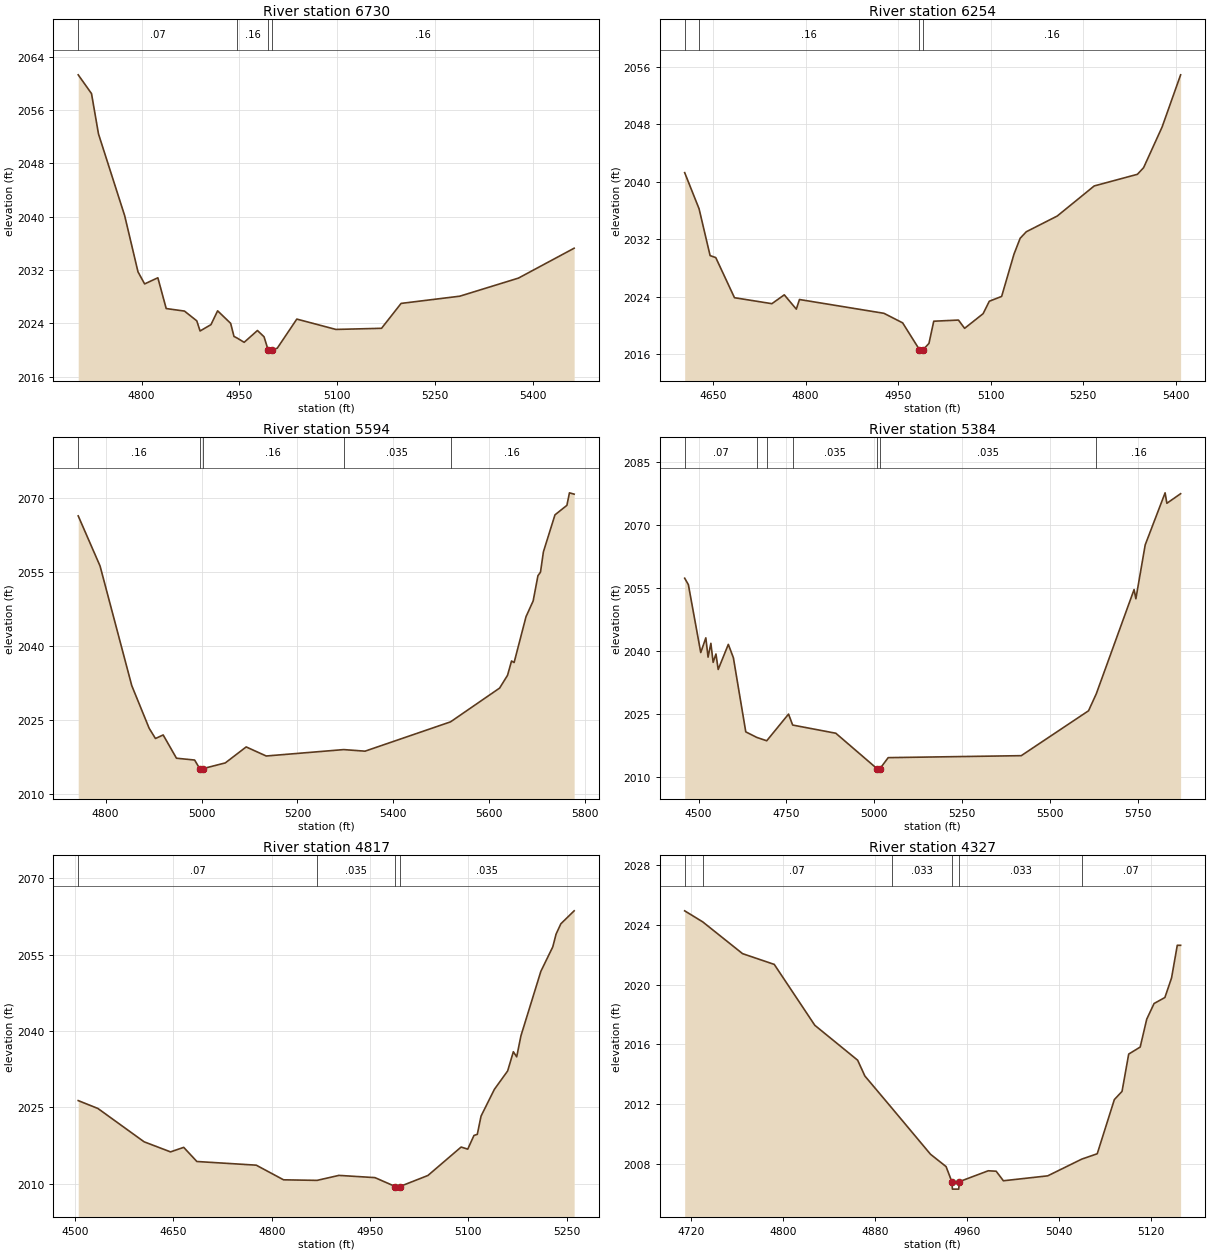
Type RM Length L Ch R = 1,6730,476,476,476
BEGIN DESCRIPTION:
139
END DESCRIPTION:
XS GIS Cut Line= 3
      1536055.03      6775988.00      1535763.16      6776044.05
      1535299.51      6776051.02
#Sta/Elev= 30
  4702.8 2061.26  4723.2 2058.45  4733.9 2052.41  4774.1 2040.15  4794.5 2031.75
  4804.7 2029.93  4825.0 2030.85  4837.8 2026.24  4865.8 2025.86  4884.7 2024.40
  4889.8 2022.88  4906.5 2023.83  4916.7 2025.90  4936.7 2024.02  4941.8 2022.06
  4946.6 2021.82  4957.4 2021.18  4977.8 2022.95  4987.9 2022.01  4994.1 2020.06
  4994.6 2019.56  5000.4 2020.06  5008.2 2020.30  5038.2 2024.66  5098.2 2023.11
  5168.2 2023.28  5198.2 2027.01  5288.2 2028.09  5378.2 2030.80  5463.7 2035.28
#Mann=4,-1,0
  4702.8    0.07       0  4946.6    0.16       0  4994.1    0.07       0
  5000.4    0.16       0
Bank Sta=4994.1,5000.4
Exp/Cntr=0.3,0.1

Type RM Length L Ch R = 1,6254,660,660,660
BEGIN DESCRIPTION:
138
END DESCRIPTION:
XS GIS Cut Line= 3
      1535954.97      6775688.00      1535562.78      6775634.60
      1535155.00      6775638.00
#Sta/Elev= 30
  4604.2 2041.30  4627.5 2036.28  4645.4 2029.76  4654.6 2029.48  4684.9 2023.90
  4745.5 2023.07  4765.6 2024.30  4785.1 2022.31  4790.2 2023.65  4927.1 2021.73
  4957.4 2020.40  4984.5 2016.69  4985.0 2016.19  4990.8 2016.69  5000.0 2017.54
  5007.8 2020.63  5047.8 2020.79  5057.8 2019.64  5087.8 2021.68  5097.8 2023.41
  5117.8 2024.08  5137.8 2029.96  5147.8 2032.17  5157.8 2033.08  5207.8 2035.26
  5267.8 2039.45  5337.8 2041.07  5347.8 2041.99  5377.8 2047.65  5407.8 2054.91
#Mann=4,-1,0
  4604.2    0.07       0  4627.5    0.16       0  4984.5    0.07       0
  4990.8    0.16       0
Bank Sta=4984.5,4990.8
Exp/Cntr=0.3,0.1

Type RM Length L Ch R = 1,5594,210,210,210
BEGIN DESCRIPTION:
137
END DESCRIPTION:
XS GIS Cut Line= 3
      1536155.02      6775588.04      1536032.15      6775362.09
      1535304.99      6775088.00
#Sta/Elev= 30
  4742.8 2066.46  4788.4 2056.28  4854.5 2032.01  4890.8 2023.35  4903.9 2021.28
  4920.0 2022.00  4947.7 2017.28  4985.6 2016.91  4996.3 2015.16  4996.8 2014.66
  5002.7 2015.16  5049.6 2016.33  5093.1 2019.57  5134.9 2017.73  5296.5 2019.03
  5341.0 2018.71  5519.3 2024.66  5621.6 2031.51  5638.2 2034.11  5646.5 2037.01
  5651.9 2036.70  5676.7 2046.00  5691.6 2049.20  5701.6 2054.32  5706.9 2055.04
  5713.0 2059.17  5737.1 2066.67  5762.0 2068.60  5767.3 2071.14  5777.1 2070.87
#Mann=5,-1,0
  4742.8    0.16       0  4996.3    0.07       0  5002.7    0.16       0
  5296.5   0.035       0  5519.3    0.16       0
Bank Sta=4996.3,5002.7
Exp/Cntr=0.3,0.1

Type RM Length L Ch R = 1,5384,567,567,567
BEGIN DESCRIPTION:
136
END DESCRIPTION:
XS GIS Cut Line= 3
      1536473.85      6775469.38      1536053.18      6775131.75
      1535188.53      6775030.19
#Sta/Elev= 30
  4460.6 2057.29  4471.1 2055.76  4506.3 2039.59  4520.7 2043.09  4527.1 2038.50
  4535.1 2041.79  4541.5 2037.26  4549.5 2039.25  4555.9 2035.57  4584.7 2041.54
  4599.1 2038.35  4634.3 2020.71  4665.5 2019.39  4693.9 2018.59  4755.9 2024.94
  4767.6 2022.33  4890.3 2020.38  5008.7 2011.86  5009.2 2011.36  5015.1 2011.86
  5039.2 2014.57  5417.5 2015.04  5608.8 2025.73  5630.8 2029.76  5738.3 2054.59
  5743.4 2052.40  5769.9 2065.22  5826.5 2077.62  5831.5 2075.13  5870.6 2077.41
#Mann=7,-1,0
  4460.6    0.07       0  4665.5   0.035       0  4693.9    0.07       0
  4767.6   0.035       0  5008.7   0.035       0  5015.1   0.035       0
  5630.8    0.16       0
Bank Sta=5008.7,5015.1
Exp/Cntr=0.3,0.1

Type RM Length L Ch R = 1,4817,490,490,490
BEGIN DESCRIPTION:
135
END DESCRIPTION:
XS GIS Cut Line= 3
      1536204.95      6774937.99      1535712.72      6774882.02
      1535454.96      6774837.99
#Sta/Elev= 30
  4504.6 2026.33  4534.7 2024.78  4605.2 2018.23  4645.5 2016.25  4665.6 2017.14
  4685.7 2014.36  4776.3 2013.64  4818.0 2010.76  4869.1 2010.65  4902.5 2011.63
  4957.5 2011.19  4988.8 2009.43  4989.3 2008.93  4995.2 2009.43  5038.3 2011.61
  5089.0 2017.20  5099.1 2016.79  5108.6 2019.48  5113.7 2019.70  5119.4 2023.28
  5139.7 2028.53  5160.0 2032.16  5168.7 2035.93  5173.8 2034.93  5180.3 2039.07
  5210.7 2051.74  5228.9 2056.55  5233.9 2059.05  5241.2 2061.08  5261.5 2063.63
#Mann=4,-1,0
  4504.6    0.07       0  4869.1   0.035       0  4988.8   0.035       0
  4995.2   0.035       0
Bank Sta=4988.8,4995.2
Exp/Cntr=0.3,0.1

Type RM Length L Ch R = 1,4327,475,475,475
BEGIN DESCRIPTION:
134
END DESCRIPTION:
XS GIS Cut Line= 3
      1536255.01      6774838.01      1536081.53      6774611.01
      1535954.99      6774537.99
#Sta/Elev= 30
  4714.3 2024.94  4730.0 2024.20  4764.7 2022.07  4792.3 2021.35  4827.6 2017.27
  4864.9 2014.93  4871.2 2013.87  4894.5 2011.74  4928.3 2008.63  4941.9 2007.80
  4946.9 2006.79  4947.4 2006.29  4952.9 2006.29  4953.4 2006.79  4978.6 2007.52
  4985.5 2007.49  4991.8 2006.85  5030.4 2007.18  5060.0 2008.30  5073.5 2008.66
  5088.4 2012.29  5095.1 2012.84  5100.9 2015.34  5110.9 2015.81  5116.6 2017.68
  5123.0 2018.73  5132.4 2019.13  5138.2 2020.44  5143.2 2022.63  5146.1 2022.63
#Mann=6,-1,0
  4714.3   0.035       0  4730.0    0.07       0  4894.5   0.033       0
  4946.9   0.033       0  4953.4   0.033       0  5060.0    0.07       0
Bank Sta=4946.9,4953.4
Exp/Cntr=0.3,0.1