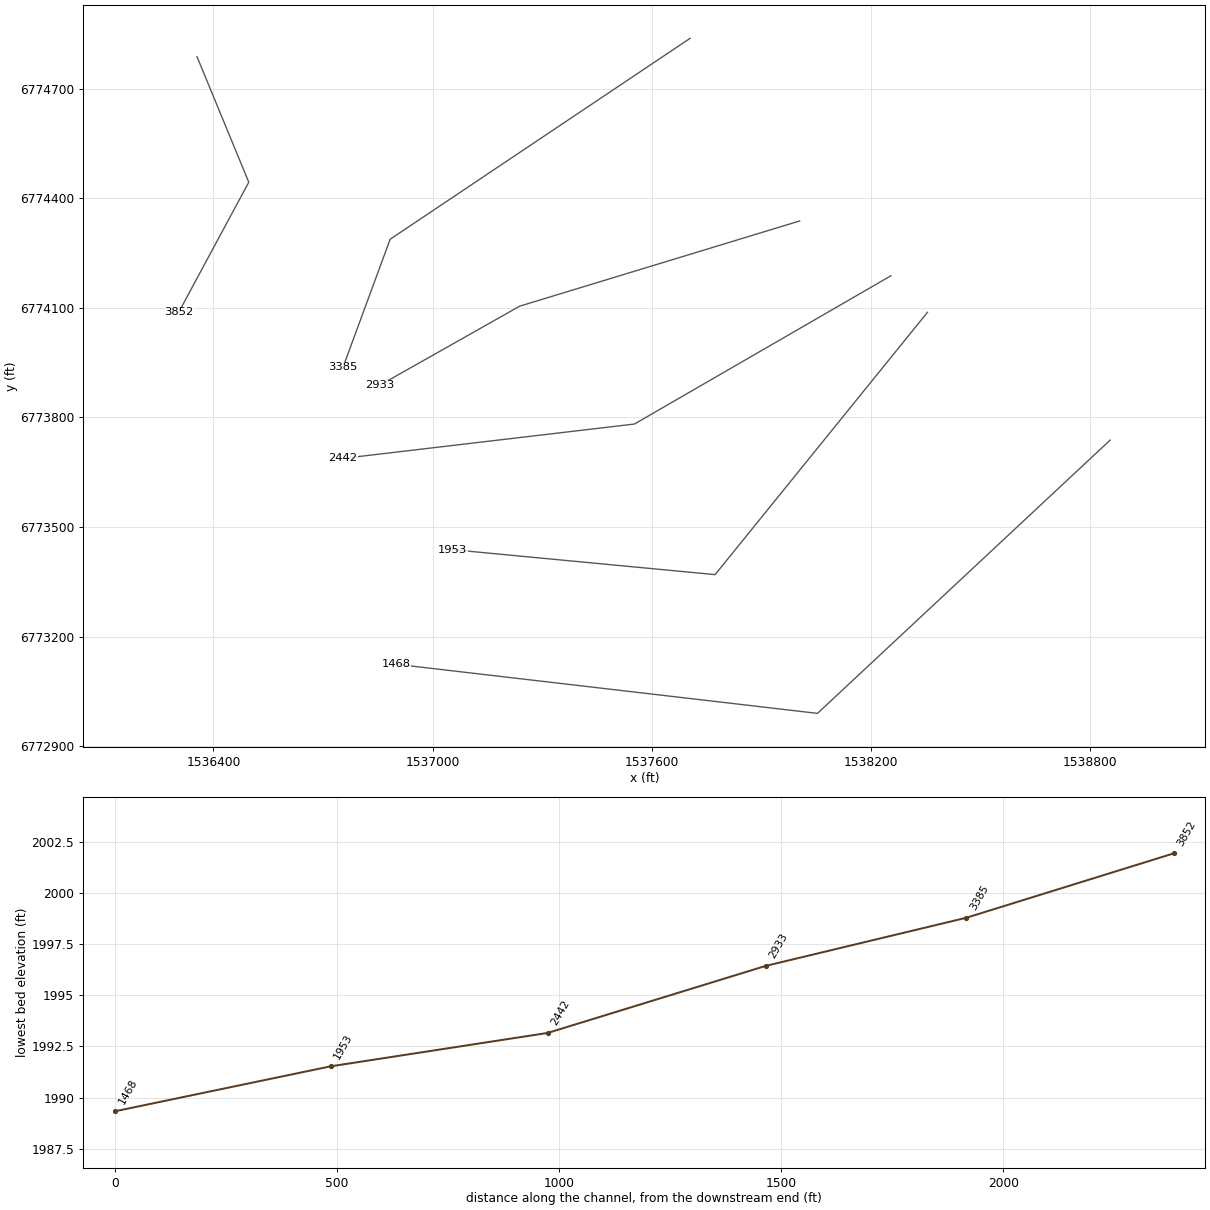
HEC-RAS study Elm 90.prj: Elm 90 Base Level Engineering

--- Elm 90.g01 (geometry) --- (continued)

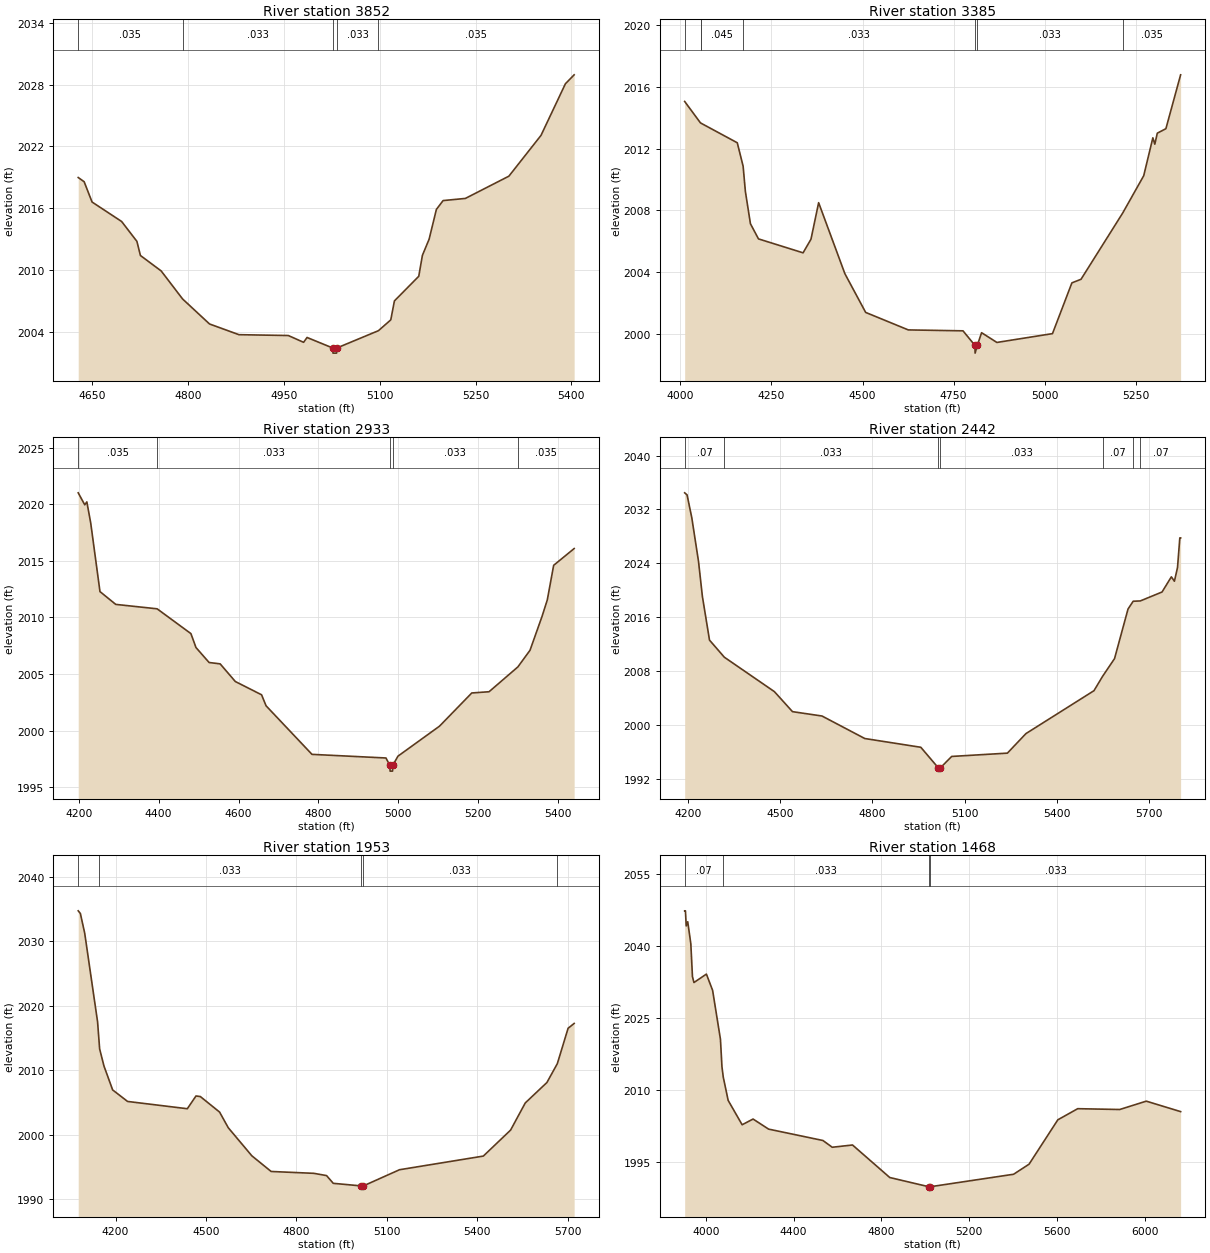
Type RM Length L Ch R = 1,3852,467,467,467
BEGIN DESCRIPTION:
133
END DESCRIPTION:
XS GIS Cut Line= 3
      1536354.98      6774788.05      1536496.84      6774444.05
      1536305.02      6774088.04
#Sta/Elev= 30
  4627.9 2018.97  4637.2 2018.56  4649.6 2016.59  4695.9 2014.70  4719.8 2012.77
  4725.3 2011.40  4757.8 2009.90  4791.3 2007.18  4833.5 2004.75  4879.6 2003.71
  4956.8 2003.63  4980.8 2002.97  4986.2 2003.44  5026.3 2002.42  5026.8 2001.92
  5032.4 2001.92  5032.9 2002.42  5098.0 2004.10  5117.3 2005.15  5123.0 2006.99
  5161.1 2009.38  5166.8 2011.41  5177.3 2012.98  5188.7 2015.87  5199.2 2016.73
  5234.1 2016.94  5302.2 2019.10  5352.5 2023.06  5390.7 2028.07  5404.4 2028.94
#Mann=5,-1,0
  4627.9   0.035       0  4791.3   0.033       0  5026.3   0.033       0
  5032.9   0.033       0  5098.0   0.035       0
Bank Sta=5026.3,5032.9
Exp/Cntr=0.3,0.1

Type RM Length L Ch R = 1,3385,452,452,452
BEGIN DESCRIPTION:
132
END DESCRIPTION:
XS GIS Cut Line= 3
      1537705.00      6774838.00      1536883.89      6774287.98
      1536754.99      6773937.96
#Sta/Elev= 30
  4011.7 2015.04  4055.2 2013.65  4055.4 2013.65  4156.1 2012.37  4172.1 2010.86
  4178.3 2009.23  4192.2 2007.14  4214.3 2006.16  4336.7 2005.26  4358.4 2006.14
  4379.4 2008.50  4451.5 2003.91  4508.5 2001.41  4625.5 2000.28  4775.7 2000.22
  4808.4 1999.28  4808.9 1998.78  4815.0 1999.28  4826.7 2000.10  4868.7 1999.47
  5021.3 2000.04  5074.6 2003.32  5099.6 2003.55  5214.0 2007.83  5271.7 2010.24
  5296.8 2012.69  5302.2 2012.28  5309.0 2012.99  5332.6 2013.28  5373.0 2016.76
#Mann=7,-1,0
  4011.7   0.045       0  4055.2   0.033       0  4055.4   0.045       0
  4172.1   0.033       0  4808.4   0.033       0  4815.0   0.033       0
  5214.0   0.035       0
Bank Sta=4808.4,4815
Exp/Cntr=0.3,0.1

Type RM Length L Ch R = 1,2933,491,491,491
BEGIN DESCRIPTION:
131
END DESCRIPTION:
XS GIS Cut Line= 3
      1538004.97      6774337.99      1537238.29      6774104.64
      1536854.98      6773887.99
#Sta/Elev= 30
  4198.6 2021.00  4215.0 2019.94  4220.2 2020.20  4229.9 2018.34  4253.1 2012.28
  4292.6 2011.15  4396.2 2010.76  4480.8 2008.57  4493.5 2007.34  4526.3 2006.02
  4554.0 2005.90  4592.0 2004.34  4657.7 2003.17  4668.9 2002.20  4783.9 1997.91
  4969.1 1997.59  4979.0 1996.93  4979.5 1996.43  4985.6 1996.43  4986.1 1996.93
  4999.1 1997.75  5103.2 2000.40  5184.0 2003.33  5227.3 2003.44  5299.4 2005.63
  5329.8 2007.10  5359.9 2010.09  5373.1 2011.55  5389.0 2014.60  5440.3 2016.08
#Mann=5,-1,0
  4198.6   0.035       0  4396.2   0.033       0  4979.0   0.033       0
  4986.1   0.033       0  5299.4   0.035       0
Bank Sta=4979,4986.1
Exp/Cntr=0.3,0.1

Type RM Length L Ch R = 1,2442,489,489,489
BEGIN DESCRIPTION:
130
END DESCRIPTION:
XS GIS Cut Line= 3
      1538254.96      6774187.98      1537552.64      6773782.03
      1536754.97      6773688.00
#Sta/Elev= 30
  4188.8 2034.47  4196.6 2034.16  4211.9 2030.79  4233.9 2024.27  4246.5 2019.08
  4269.6 2012.61  4317.9 2010.07  4480.9 2004.96  4539.7 2001.99  4635.9 2001.34
  4775.1 1998.00  4957.5 1996.70  5014.2 1993.66  5014.7 1993.16  5021.4 1993.66
  5058.0 1995.34  5239.3 1995.83  5299.7 1998.73  5521.2 2005.10  5549.5 2007.25
  5588.1 2009.86  5632.0 2017.22  5648.8 2018.38  5671.8 2018.42  5742.8 2019.75
  5773.0 2022.00  5783.0 2021.35  5793.1 2023.38  5800.6 2027.78  5803.2 2027.78
#Mann=7,-1,0
  4188.8    0.07       0  4317.9   0.033       0  5014.2   0.033       0
  5021.4   0.033       0  5549.5    0.07       0  5648.8   0.035       0
  5671.8    0.07       0
Bank Sta=5014.2,5021.4
Exp/Cntr=0.3,0.1

Type RM Length L Ch R = 1,1953,485,485,485
BEGIN DESCRIPTION:
129
END DESCRIPTION:
XS GIS Cut Line= 3
      1538354.99      6774087.99      1537773.54      6773369.75
      1537054.97      6773438.00
#Sta/Elev= 30
  4075.9 2034.73  4083.1 2034.32  4097.5 2031.25  4140.2 2017.49  4145.0 2014.53
  4147.0 2013.29  4161.4 2010.64  4190.2 2006.93  4239.7 2005.14  4438.0 2004.01
  4466.8 2005.99  4481.2 2005.90  4545.1 2003.49  4573.9 2001.06  4652.2 1996.70
  4716.2 1994.27  4858.4 1993.98  4900.1 1993.63  4922.4 1992.43  5015.0 1992.03
  5015.5 1991.53  5022.2 1992.03  5142.2 1994.54  5420.4 1996.66  5510.8 2000.69
  5559.6 2004.91  5631.4 2008.08  5666.0 2011.01  5701.7 2016.50  5721.8 2017.25
#Mann=5,-1,0
  4075.9   0.035       0  4145.0   0.033       0  5015.0   0.033       0
  5022.2   0.033       0  5666.0   0.035       0
Bank Sta=5015,5022.2
Exp/Cntr=0.3,0.1

Type RM Length L Ch R = 1,1468,0,0,0
BEGIN DESCRIPTION:
128
END DESCRIPTION:
XS GIS Cut Line= 3
      1538854.97      6773737.97      1538053.84      6772989.88
      1536899.66      6773124.41
#Sta/Elev= 30
  3903.9 2047.36  3907.3 2047.36  3910.9 2044.22  3917.8 2045.08  3931.9 2040.50
  3939.3 2033.66  3946.1 2032.41  4002.8 2034.17  4031.1 2030.78  4066.8 2020.58
  4073.6 2014.87  4079.7 2012.67  4101.9 2007.84  4165.5 2002.76  4215.3 2003.95
  4286.1 2001.85  4533.3 1999.48  4575.8 1998.07  4668.1 1998.54  4837.7 1991.76
  5015.3 1989.84  5015.8 1989.34  5022.6 1989.84  5401.5 1992.44  5472.0 1994.54
  5602.9 2003.79  5693.5 2006.11  5884.8 2005.94  6005.6 2007.68  6162.0 2005.50
#Mann=4,-1,0
  3903.9    0.07       0  4079.7   0.033       0  5015.3   0.033       0
  5022.6   0.033       0
Bank Sta=5015.3,5022.6
Exp/Cntr=0.3,0.1

Chan Stop Cuts=-1