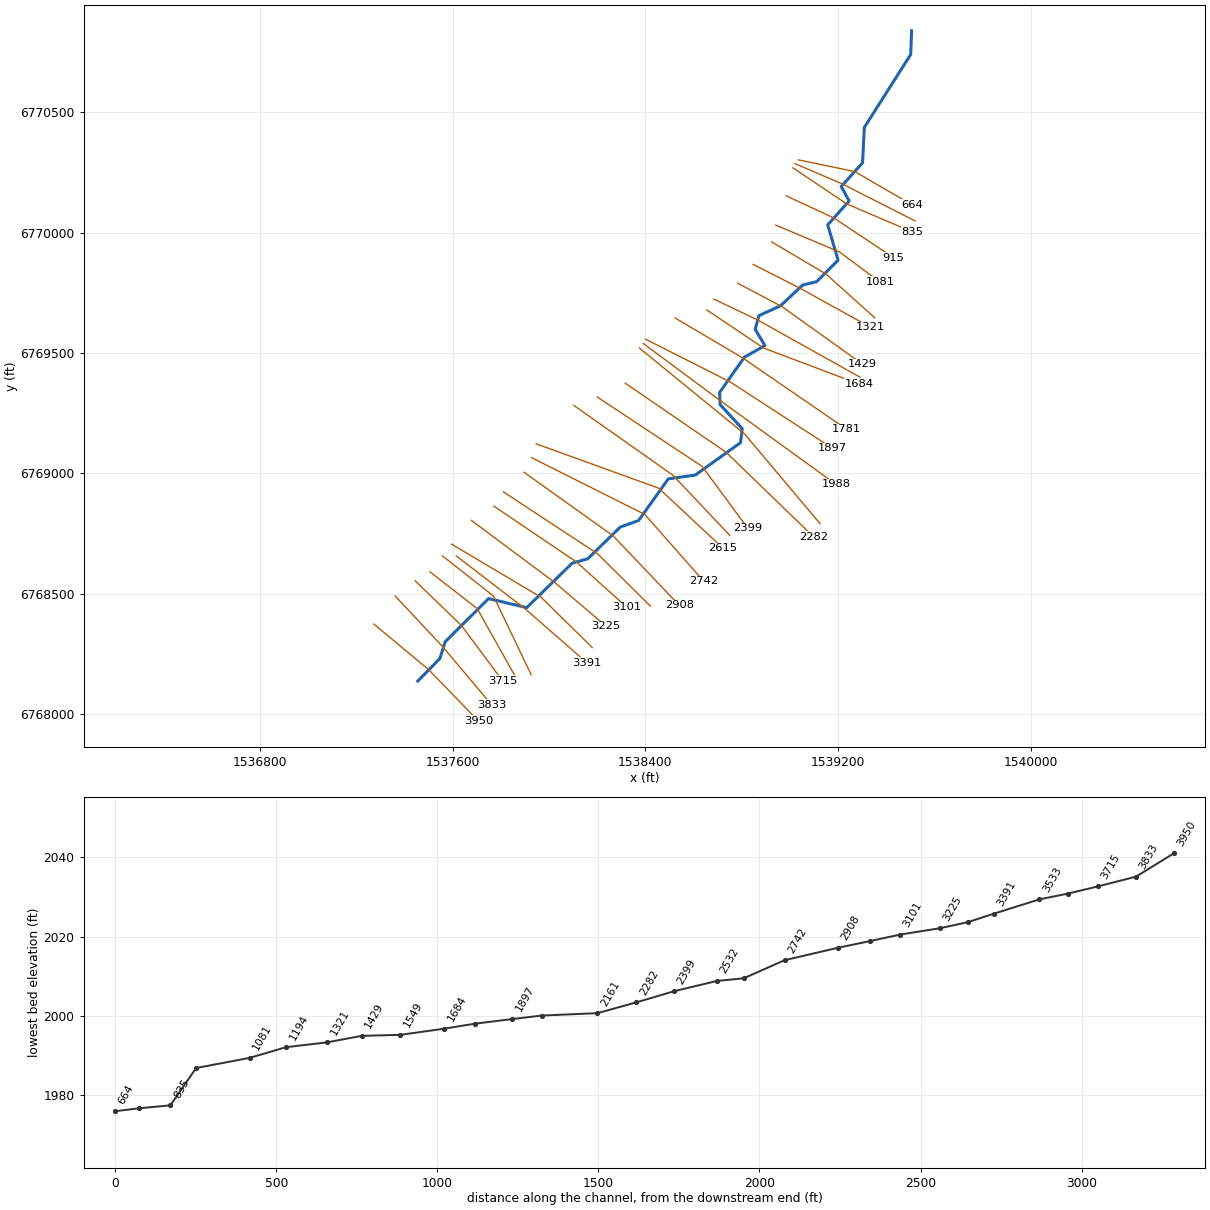
--- Elm 91.prj (project) ---

Proj Title=Elm 91 Base Level Engineering
Current Plan=p01
Default Exp/Contr=0.3,0.1
English Units
Geom File=g01
Flow File=f01
Plan File=p01
BEGIN DESCRIPTION:
Elm 91
END DESCRIPTION:

--- Elm 91.p01 (plan) ---

Plan Title=Multiple Run
Short Identifier=Multiple
Geom File=g01
Flow File=f01
Subcritical Flow
K Sum by GR= 0
Std Step Tol= 0.01
Critical Tol= 0.01
Num of Std Step Trials= 20
Max Error Tol= 0.3
Flow Tol Ratio= 0.001
Split Flow NTrial= 30
Split Flow Tol= 0.02
Split Flow Ratio= 0.02
Log Output Level= 0
Friction Slope Method= 1
Unsteady Friction Slope Method= 2
Unsteady Bridges Friction Slope Method= 1
Parabolic Critical Depth
Global Vel Dist=  1 , 1 , 1
Global Log Level= 0
CheckData=True
Encroach Param= -1, 0, 0, 0
BEGIN DESCRIPTION:
Multiple Run
END DESCRIPTION:

--- Elm 91.f01 (steady flow) ---

Flow Title=Multiple
Number of Profiles=7
Profile Names=10-year,25-year,50-year,1pct_min,100-year,1pct_plu,500-year
River Rch & RM= Elm 91,Reach-1,3950
     117     155     186     139     222     306     321
Boundary for River Rch & Prof#=Elm 91,Reach-1,1
Up Type=0
Dn Type=3
Dn Slope=0.005
Boundary for River Rch & Prof#=Elm 91,Reach-1,2
Up Type=0
Dn Type=3
Dn Slope=0.005
Boundary for River Rch & Prof#=Elm 91,Reach-1,3
Up Type=0
Dn Type=3
Dn Slope=0.005
Boundary for River Rch & Prof#=Elm 91,Reach-1,4
Up Type=0
Dn Type=3
Dn Slope=0.005
Boundary for River Rch & Prof#=Elm 91,Reach-1,5
Up Type=0
Dn Type=3
Dn Slope=0.005
Boundary for River Rch & Prof#=Elm 91,Reach-1,6
Up Type=0
Dn Type=3
Dn Slope=0.005
Boundary for River Rch & Prof#=Elm 91,Reach-1,7
Up Type=0
Dn Type=3
Dn Slope=0.005

--- Elm 91.g01 (geometry) ---

Geom Title=Existing Conditions

River Reach=Elm 91,Reach-1
Reach XY= 30
      1537455.00      6768138.00      1537546.89      6768231.93
      1537568.63      6768301.21      1537748.94      6768480.52
      1537907.30      6768443.09      1538095.32      6768627.22
      1538161.05      6768646.16      1538295.32      6768777.22
      1538371.71      6768804.64      1538494.90      6768977.61
      1538607.42      6768993.54      1538794.96      6769128.00
      1538801.90      6769186.32      1538710.08      6769285.72
      1538708.11      6769336.35      1538810.68      6769482.38
      1538895.92      6769531.01      1538855.87      6769598.68
      1538871.07      6769655.05      1538961.02      6769696.18
      1539052.72      6769782.13      1539111.07      6769796.15
      1539199.91      6769885.69      1539156.64      6770031.96
      1539245.68      6770131.34      1539213.02      6770191.33
      1539301.43      6770289.47      1539308.76      6770436.44
      1539501.37      6770739.50      1539505.00      6770838.00

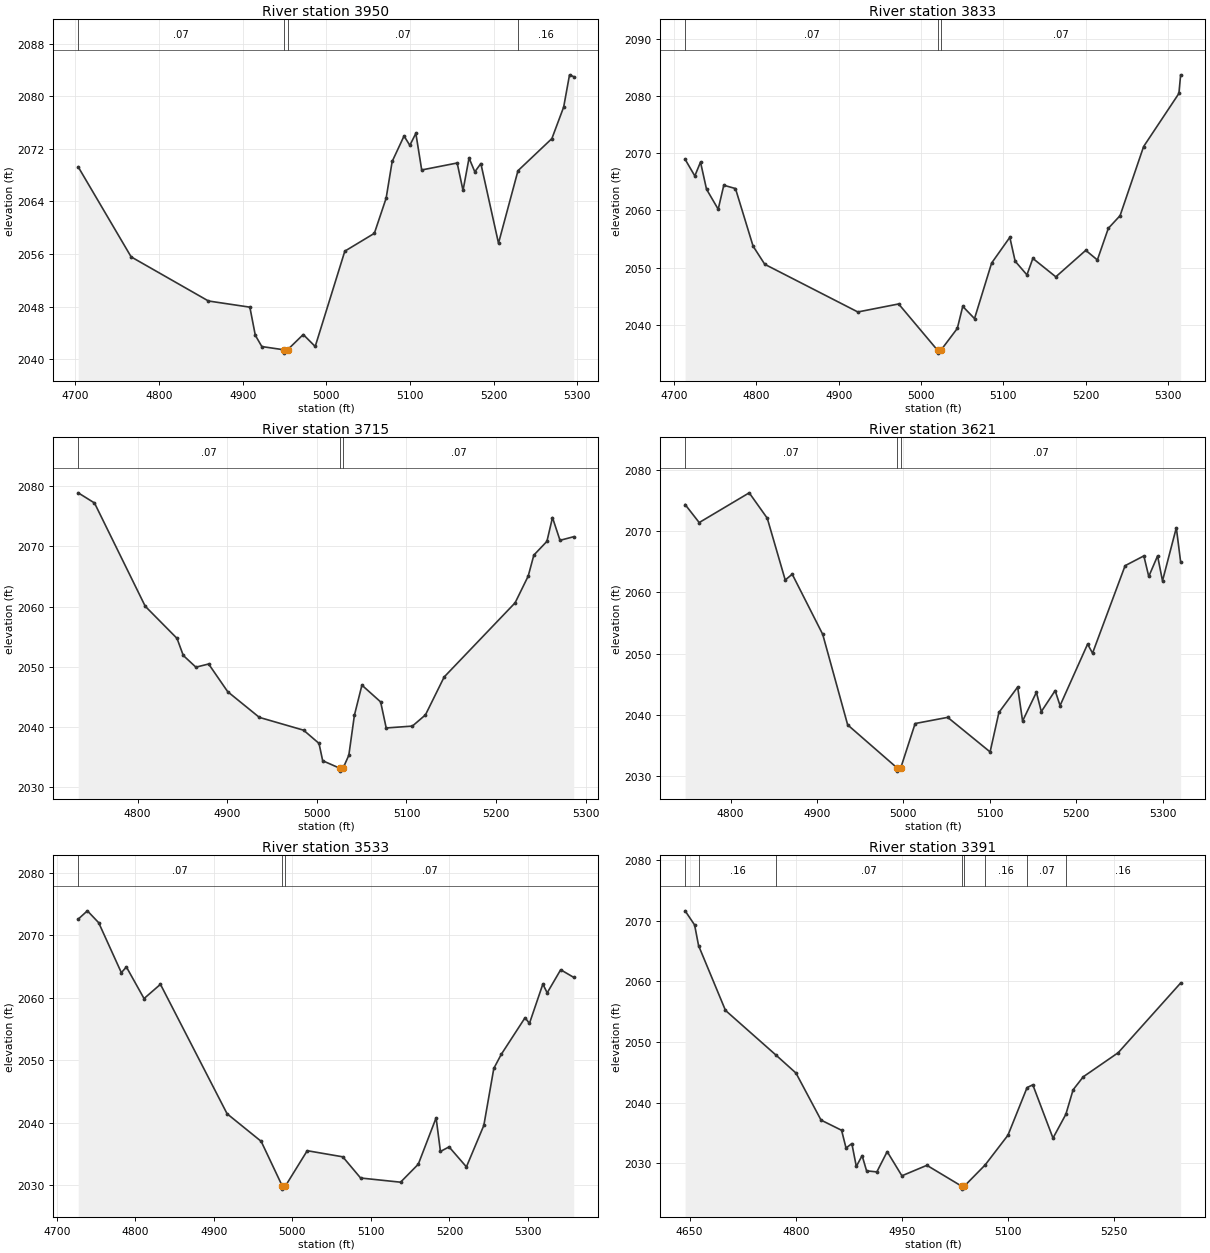
Type RM Length L Ch R = 1,3950,117,117,117
BEGIN DESCRIPTION:
Elm 91 3966
END DESCRIPTION:
XS GIS Cut Line= 3
      1537272.89      6768374.76      1537500.95      6768184.97
      1537706.44      6767972.48
#Sta/Elev= 30
  4703.3 2069.26  4766.6 2055.57  4859.0 2048.86  4908.5 2047.92  4915.0 2043.65
  4922.8 2041.93  4949.5 2041.43  4949.7 2040.93  4953.5 2041.43  4972.3 2043.76
  4986.6 2041.94  5022.0 2056.44  5057.3 2059.15  5071.4 2064.50  5078.6 2070.08
  5092.8 2073.96  5099.7 2072.53  5106.9 2074.36  5113.9 2068.79  5156.3 2069.85
  5163.3 2065.67  5170.5 2070.61  5177.4 2068.50  5184.6 2069.77  5205.7 2057.65
  5229.0 2068.68  5269.5 2073.56  5283.6 2078.36  5290.6 2083.26  5295.6 2082.98
#Mann=4,-1,0
  4703.3    0.07       0  4949.5    0.07       0  4953.5    0.07       0
  5229.0    0.16       0
Bank Sta=4949.5,4953.5
Exp/Cntr=0.3,0.1

Type RM Length L Ch R = 1,3833,118,118,118
BEGIN DESCRIPTION:
Elm 91 3833.174
END DESCRIPTION:
XS GIS Cut Line= 3
      1537361.41      6768491.10      1537557.52      6768281.96
      1537760.72      6768040.60
#Sta/Elev= 30
  4713.3 2068.93  4725.1 2066.02  4732.0 2068.45  4739.3 2063.71  4753.5 2060.21
  4760.3 2064.40  4774.5 2063.82  4795.9 2053.76  4810.1 2050.59  4923.2 2042.26
  4972.8 2043.66  5020.1 2035.57  5020.3 2035.07  5024.1 2035.57  5044.1 2039.39
  5050.7 2043.24  5065.0 2041.10  5085.8 2050.81  5107.9 2055.30  5114.4 2051.13
  5128.7 2048.74  5135.9 2051.62  5163.8 2048.40  5200.2 2053.03  5214.3 2051.35
  5227.6 2056.87  5241.9 2059.09  5270.5 2071.16  5313.4 2080.44  5315.5 2083.69
#Mann=3,-1,0
  4713.3    0.07       0  5020.1    0.07       0  5024.1    0.07       0
Bank Sta=5020.1,5024.1
Exp/Cntr=0.3,0.1

Type RM Length L Ch R = 1,3715,94,94,94
BEGIN DESCRIPTION:
Elm 91 3715.33
END DESCRIPTION:
XS GIS Cut Line= 3
      1537444.74      6768553.61      1537635.72      6768369.56
      1537807.61      6768138.64
#Sta/Elev= 30
  4733.6 2078.91  4751.8 2077.22  4808.4 2060.05  4843.9 2054.70  4850.9 2051.86
  4865.0 2049.91  4879.2 2050.44  4900.5 2045.83  4935.8 2041.56  4985.2 2039.43
  5002.4 2037.23  5006.5 2034.35  5025.3 2033.12  5025.6 2032.62  5029.3 2033.12
  5035.7 2035.27  5041.9 2041.91  5050.3 2046.92  5071.2 2044.13  5077.4 2039.80
  5106.6 2040.11  5121.2 2041.97  5142.1 2048.28  5221.3 2060.62  5235.9 2065.06
  5242.2 2068.55  5256.8 2070.84  5263.0 2074.80  5271.4 2071.01  5286.7 2071.61
#Mann=3,-1,0
  4733.6    0.07       0  5025.3    0.07       0  5029.3    0.07       0
Bank Sta=5025.3,5029.3
Exp/Cntr=0.3,0.1

Type RM Length L Ch R = 1,3621,88,88,88
BEGIN DESCRIPTION:
Elm 91 3620.5
END DESCRIPTION:
XS GIS Cut Line= 3
      1537505.50      6768591.80      1537701.70      6768439.01
      1537860.72      6768155.54
#Sta/Elev= 30
  4747.3 2074.38  4763.6 2071.43  4821.5 2076.29  4842.4 2072.14  4863.2 2062.04
  4871.3 2062.99  4906.6 2053.16  4935.5 2038.36  4992.9 2031.30  4993.1 2030.80
  4996.9 2031.30  5013.6 2038.58  5051.3 2039.59  5100.4 2033.94  5110.6 2040.39
  5132.3 2044.54  5138.0 2038.99  5154.0 2043.69  5159.7 2040.53  5175.7 2043.96
  5181.4 2041.51  5213.3 2051.57  5219.0 2050.08  5256.7 2064.38  5278.4 2065.98
  5284.1 2062.62  5294.3 2065.98  5300.0 2061.90  5316.0 2070.58  5321.0 2065.00
#Mann=3,-1,0
  4747.3    0.07       0  4992.9    0.07       0  4996.9    0.07       0
Bank Sta=4992.9,4996.9
Exp/Cntr=0.3,0.1

Type RM Length L Ch R = 1,3533,142,142,142
BEGIN DESCRIPTION:
Elm 91 3533.43
END DESCRIPTION:
XS GIS Cut Line= 3
      1537557.63      6768657.74      1537769.41      6768491.09
      1537925.64      6768164.74
#Sta/Elev= 30
  4727.1 2072.56  4738.8 2073.89  4753.2 2071.99  4782.1 2063.99  4788.5 2064.91
  4811.0 2059.85  4831.9 2062.13  4916.8 2041.41  4960.2 2037.00  4987.1 2029.85
  4987.3 2029.35  4991.1 2029.85  5018.9 2035.50  5064.2 2034.52  5086.9 2031.13
  5137.8 2030.46  5160.4 2033.34  5183.1 2040.76  5188.6 2035.38  5199.6 2036.11
  5221.7 2032.91  5243.9 2039.55  5256.6 2048.67  5266.1 2050.92  5296.4 2056.78
  5302.0 2055.87  5319.1 2062.17  5324.6 2060.76  5341.8 2064.46  5358.4 2063.24
#Mann=3,-1,0
  4727.1    0.07       0  4987.1    0.07       0  4991.1    0.07       0
Bank Sta=4987.1,4991.1
Exp/Cntr=0.3,0.1

Type RM Length L Ch R = 1,3391,81,81,81
BEGIN DESCRIPTION:
Elm 91 3390.61
END DESCRIPTION:
XS GIS Cut Line= 3
      1537614.89      6768657.75      1537899.61      6768439.01
      1538156.56      6768215.05
#Sta/Elev= 30
  4643.7 2071.65  4657.1 2069.32  4662.7 2065.91  4700.7 2055.22  4772.4 2047.81
  4800.3 2044.88  4835.7 2037.12  4864.7 2035.44  4871.0 2032.51  4879.2 2033.25
  4885.5 2029.47  4893.7 2031.26  4900.0 2028.75  4914.5 2028.57  4929.1 2031.92
  4949.9 2027.93  4985.2 2029.66  5034.1 2026.23  5034.3 2025.73  5038.1 2026.23
  5067.4 2029.71  5099.7 2034.63  5126.7 2042.49  5134.8 2042.94  5163.3 2034.15
  5181.5 2038.08  5191.7 2042.12  5206.0 2044.26  5255.4 2048.24  5343.6 2059.74
#Mann=8,-1,0
  4643.7    0.07       0  4662.7    0.16       0  4772.4    0.07       0
  5034.1    0.07       0  5038.1    0.07       0  5067.4    0.16       0
  5126.7    0.07       0  5181.5    0.16       0
Bank Sta=5034.1,5038.1
Exp/Cntr=0.3,0.1

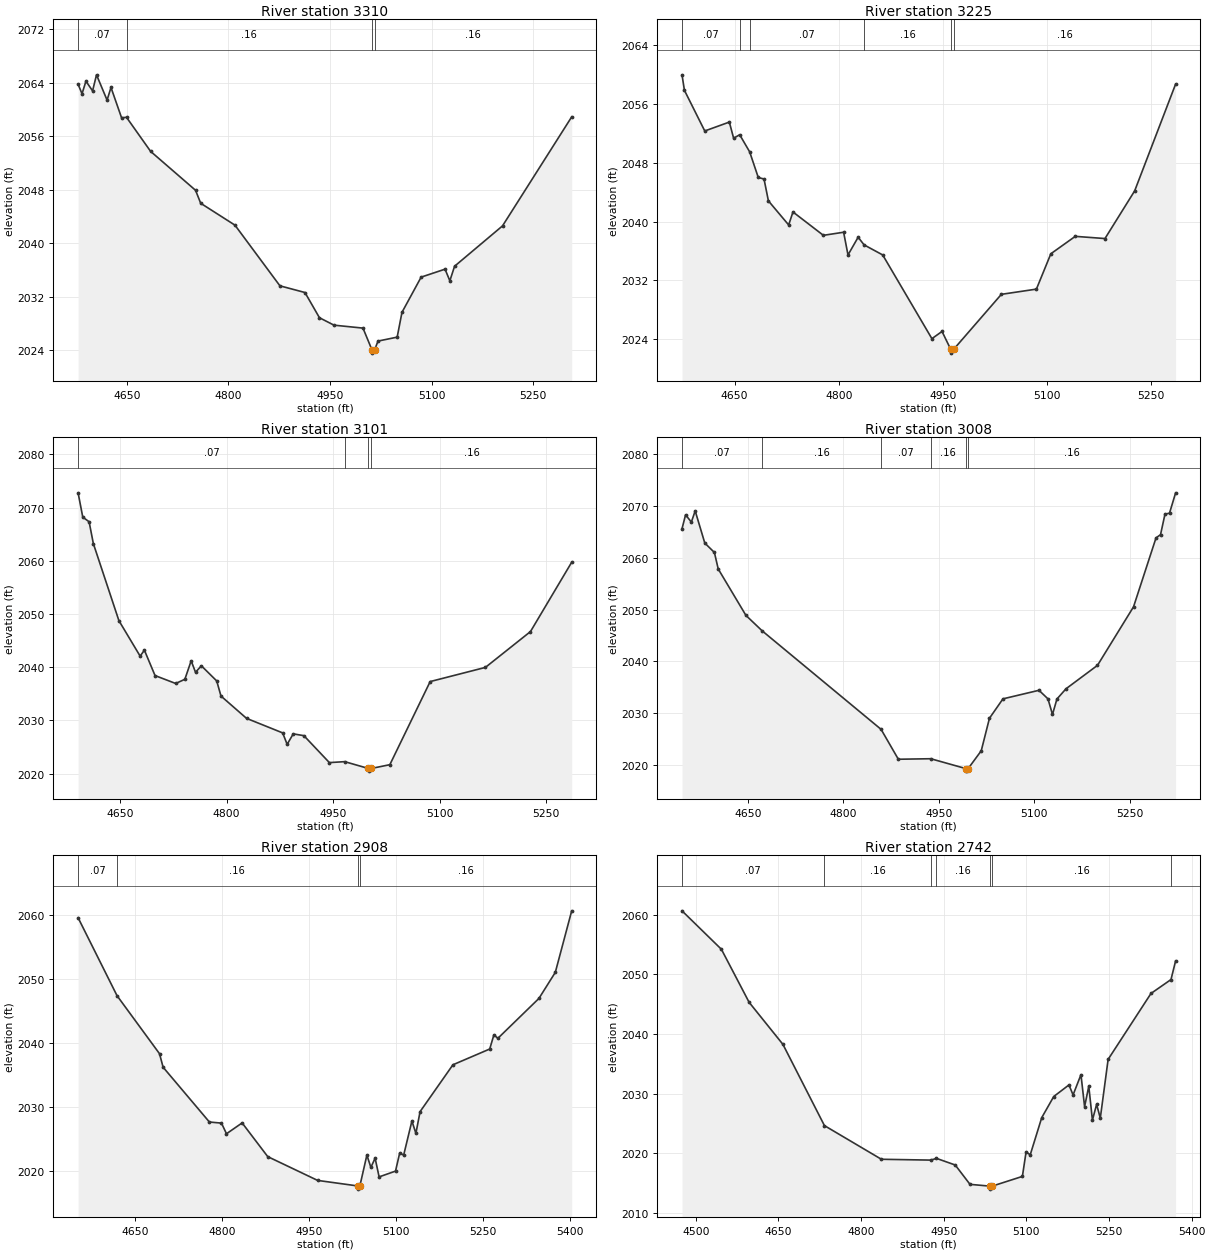
Type RM Length L Ch R = 1,3310,85,85,85
BEGIN DESCRIPTION:
Elm 91 3310.09
END DESCRIPTION:
XS GIS Cut Line= 3
      1537595.78      6768706.37      1537967.32      6768485.88
      1538179.11      6768277.57
#Sta/Elev= 30
  4577.9 2063.78  4583.7 2062.36  4589.5 2064.24  4599.3 2062.79  4605.1 2065.19
  4620.7 2061.41  4626.5 2063.30  4642.1 2058.77  4649.4 2058.84  4685.0 2053.75
  4751.4 2047.93  4759.0 2045.99  4809.6 2042.72  4876.0 2033.65  4913.0 2032.65
  4934.4 2028.88  4955.9 2027.77  4998.7 2027.33  5011.9 2024.09  5012.1 2023.59
  5015.9 2024.09  5020.9 2025.39  5049.2 2025.98  5056.3 2029.69  5084.6 2034.95
  5119.9 2036.14  5127.0 2034.40  5134.0 2036.58  5204.8 2042.61  5307.0 2058.91
#Mann=4,-1,0
  4577.9    0.07       0  4649.4    0.16       0  5011.9    0.07       0
  5015.9    0.16       0
Bank Sta=5011.9,5015.9
Exp/Cntr=0.3,0.1

Type RM Length L Ch R = 1,3225,124,124,124
BEGIN DESCRIPTION:
Elm 91 3225.2
END DESCRIPTION:
XS GIS Cut Line= 3
      1537677.41      6768805.31      1538024.61      6768546.65
      1538236.43      6768366.08
#Sta/Elev= 30
  4574.2 2059.97  4577.7 2057.86  4607.0 2052.33  4642.4 2053.54  4648.6 2051.34
  4657.3 2051.82  4671.7 2049.49  4684.1 2046.00  4692.4 2045.79  4698.7 2042.82
  4727.9 2039.54  4734.1 2041.31  4777.9 2038.13  4807.1 2038.55  4813.4 2035.46
  4828.0 2037.87  4836.6 2036.83  4863.4 2035.46  4934.3 2024.07  4948.9 2025.05
  4961.5 2022.60  4961.8 2022.10  4965.5 2022.60  5034.4 2030.10  5084.9 2030.81
  5105.7 2035.62  5140.9 2037.99  5183.7 2037.69  5226.5 2044.18  5285.5 2058.71
#Mann=6,-1,0
  4574.2    0.07       0  4657.3    0.16       0  4671.7    0.07       0
  4836.6    0.16       0  4961.5    0.07       0  4965.5    0.16       0
Bank Sta=4961.5,4965.5
Exp/Cntr=0.3,0.1

Type RM Length L Ch R = 1,3101,93,93,93
BEGIN DESCRIPTION:
Elm 91 3100.51
END DESCRIPTION:
XS GIS Cut Line= 3
      1537771.12      6768864.37      1538114.89      6768631.72
      1538323.24      6768444.20
#Sta/Elev= 30
  4590.7 2072.76  4597.3 2068.19  4606.2 2067.33  4612.2 2063.22  4648.2 2048.75
  4678.1 2042.09  4684.1 2043.21  4699.1 2038.44  4728.2 2036.95  4741.1 2037.74
  4750.0 2041.21  4756.1 2039.06  4764.4 2040.27  4786.0 2037.43  4792.0 2034.59
  4828.0 2030.40  4878.9 2027.67  4885.2 2025.52  4893.8 2027.49  4908.8 2027.15
  4944.7 2022.09  4966.3 2022.27  4999.7 2020.99  4999.9 2020.49  5003.7 2020.99
  5029.9 2021.70  5086.7 2037.31  5164.5 2039.97  5228.0 2046.70  5286.1 2059.73
#Mann=4,-1,0
  4590.7    0.07       0  4966.3    0.16       0  4999.7    0.07       0
  5003.7    0.16       0
Bank Sta=4999.7,5003.7
Exp/Cntr=0.3,0.1

Type RM Length L Ch R = 1,3008,100,100,100
BEGIN DESCRIPTION:
Elm 91 3007.71
END DESCRIPTION:
XS GIS Cut Line= 3
      1537811.11      6768923.36      1538201.70      6768666.44
      1538420.20      6768449.67
#Sta/Elev= 30
  4546.7 2065.57  4552.3 2068.26  4561.4 2066.86  4567.4 2069.02  4582.5 2062.82
  4597.6 2061.00  4603.6 2057.82  4647.1 2048.88  4672.5 2045.91  4859.4 2026.91
  4886.5 2021.15  4937.4 2021.25  4992.2 2019.36  4992.5 2018.86  4996.2 2019.36
  5016.7 2022.78  5029.6 2029.05  5050.8 2032.79  5107.4 2034.44  5121.5 2032.79
  5128.6 2029.78  5135.6 2032.76  5149.8 2034.73  5199.3 2039.25  5255.9 2050.53
  5291.2 2063.81  5298.3 2064.44  5305.3 2068.39  5312.4 2068.58  5322.0 2072.50
#Mann=6,-1,0
  4546.7    0.07       0  4672.5    0.16       0  4859.4    0.07       0
  4937.4    0.16       0  4992.2    0.07       0  4996.2    0.16       0
Bank Sta=4992.2,4996.2
Exp/Cntr=0.3,0.1

Type RM Length L Ch R = 1,2908,166,166,166
BEGIN DESCRIPTION:
Elm 91 2907.51
END DESCRIPTION:
XS GIS Cut Line= 3
      1537896.13      6769004.99      1538265.93      6768741.09
      1538540.09      6768453.14
#Sta/Elev= 30
  4551.1 2059.51  4618.3 2047.35  4691.6 2038.30  4697.8 2036.19  4777.7 2027.64
  4798.5 2027.47  4807.2 2025.81  4834.2 2027.50  4878.4 2022.24  4964.5 2018.53
  5033.4 2017.67  5033.6 2017.17  5037.4 2017.67  5049.5 2022.48  5056.4 2020.56
  5063.7 2022.00  5070.6 2019.08  5098.9 2019.98  5106.1 2022.79  5113.0 2022.48
  5127.2 2027.80  5134.1 2025.87  5141.3 2029.26  5198.0 2036.57  5261.5 2039.03
  5268.7 2041.24  5275.6 2040.70  5346.4 2046.92  5374.7 2050.99  5403.0 2060.59
#Mann=4,-1,0
  4551.1    0.07       0  4618.3    0.16       0  5033.4    0.07       0
  5037.4    0.16       0
Bank Sta=5033.4,5037.4
Exp/Cntr=0.3,0.1

Type RM Length L Ch R = 1,2742,127,127,127
BEGIN DESCRIPTION:
Elm 91 2741.69
END DESCRIPTION:
XS GIS Cut Line= 3
      1537927.38      6769065.75      1538397.88      6768829.63
      1538642.16      6768552.43
#Sta/Elev= 30
  4475.0 2060.64  4546.5 2054.20  4596.8 2045.32  4658.2 2038.27  4733.5 2024.67
  4836.9 2019.03  4926.7 2018.89  4936.9 2019.18  4970.9 2018.07  4997.7 2014.83
  5033.9 2014.53  5034.1 2014.03  5037.9 2014.53  5092.8 2016.16  5099.5 2020.27
  5107.0 2019.77  5127.9 2026.00  5149.7 2029.54  5177.3 2031.48  5184.8 2029.81
  5199.1 2033.20  5205.7 2027.84  5213.3 2031.27  5219.9 2025.59  5227.5 2028.22
  5234.2 2025.92  5248.4 2035.76  5326.2 2046.80  5362.5 2049.13  5370.9 2052.26
#Mann=7,-1,0
  4475.0    0.07       0  4733.5    0.16       0  4926.7    0.07       0
  4936.9    0.16       0  5033.9    0.07       0  5037.9    0.16       0
  5362.5    0.07       0
Bank Sta=5033.9,5037.9
Exp/Cntr=0.3,0.1

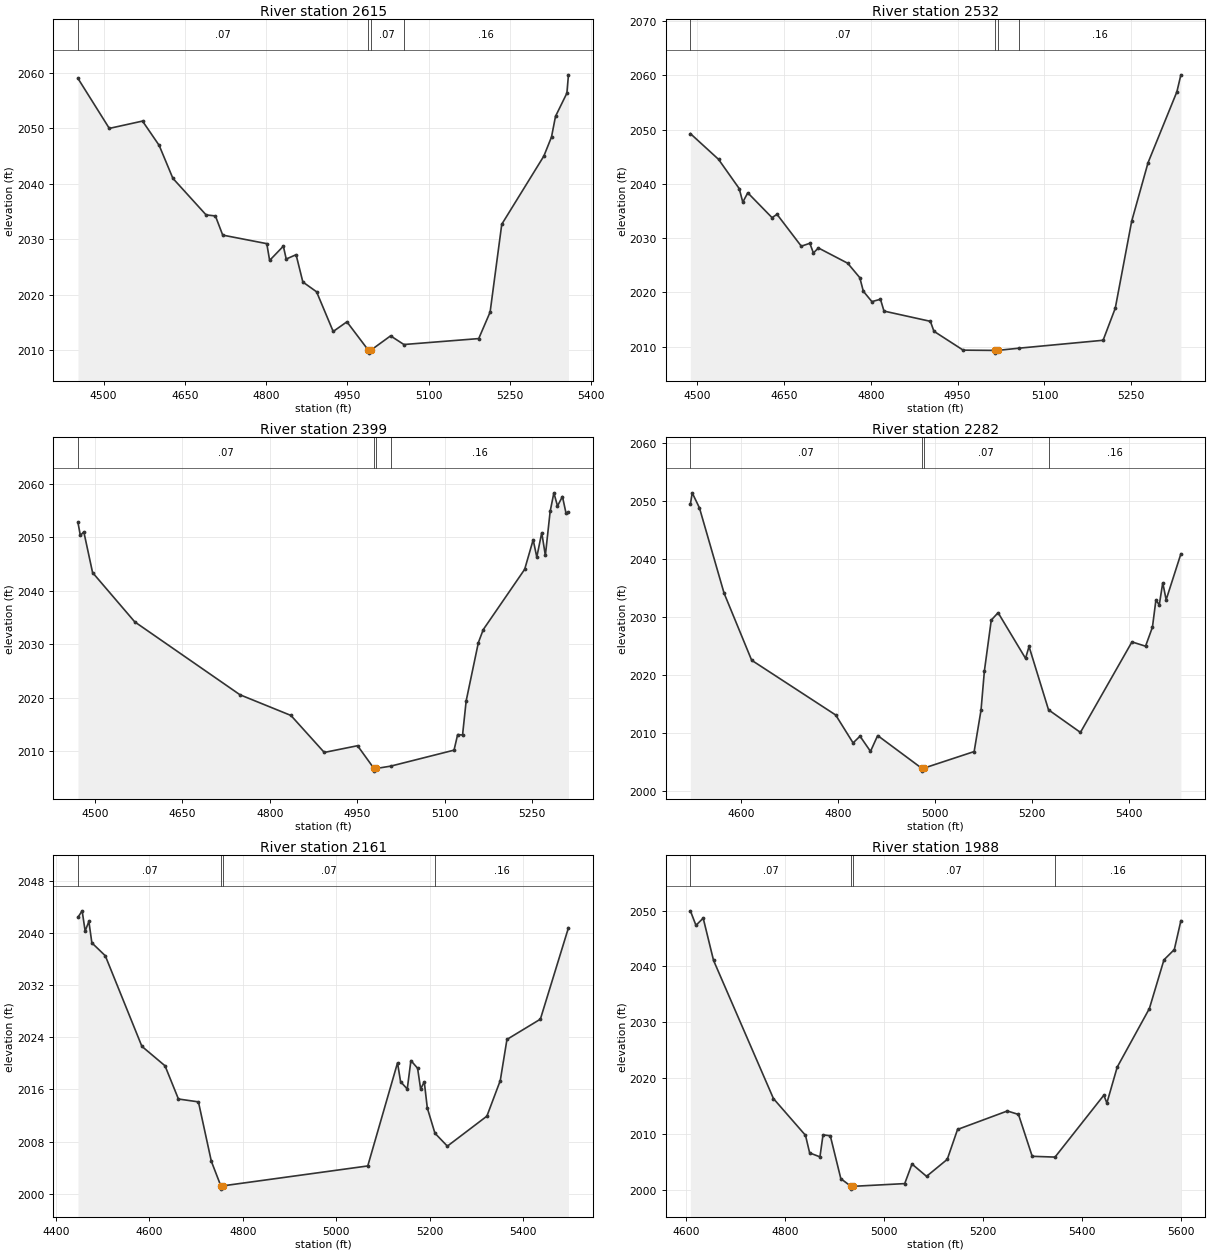
Type RM Length L Ch R = 1,2615,83,83,83
BEGIN DESCRIPTION:
Elm 91 2614.93
END DESCRIPTION:
XS GIS Cut Line= 3
      1537946.45      6769123.05      1538455.17      6768939.01
      1538721.27      6768690.19
#Sta/Elev= 30
  4452.8 2058.96  4510.7 2049.95  4572.0 2051.27  4602.7 2046.89  4628.0 2040.96
  4689.3 2034.37  4706.5 2034.18  4720.0 2030.73  4801.3 2029.19  4806.6 2026.17
  4831.9 2028.74  4837.2 2026.42  4855.4 2027.20  4867.9 2022.28  4893.2 2020.52
  4923.9 2013.37  4949.2 2015.11  4989.0 2009.97  4989.3 2009.47  4993.0 2009.97
  5029.8 2012.58  5054.4 2011.02  5192.5 2012.09  5213.5 2016.86  5235.0 2032.68
  5312.7 2044.97  5326.8 2048.40  5334.2 2052.12  5355.2 2056.30  5358.1 2059.60
#Mann=4,-1,0
  4452.8    0.07       0  4989.0    0.07       0  4993.0    0.07       0
  5054.4    0.16       0
Bank Sta=4989,4993
Exp/Cntr=0.3,0.1

Type RM Length L Ch R = 1,2532,133,133,133
BEGIN DESCRIPTION:
Elm 91 2531.65
END DESCRIPTION:
XS GIS Cut Line= 3
      1538102.74      6769282.76      1538514.20      6768992.83
      1538750.09      6768743.06
#Sta/Elev= 30
  4488.6 2049.27  4537.2 2044.53  4572.9 2039.14  4579.1 2036.63  4587.7 2038.36
  4629.6 2033.78  4638.2 2034.39  4680.1 2028.52  4694.9 2029.05  4701.0 2027.27
  4709.7 2028.19  4760.2 2025.38  4781.1 2022.72  4787.2 2020.22  4802.0 2018.30
  4816.8 2018.74  4822.9 2016.56  4903.0 2014.67  4909.1 2012.84  4959.6 2009.36
  5015.1 2009.31  5015.3 2008.81  5019.1 2009.31  5055.8 2009.72  5201.2 2011.18
  5222.2 2017.09  5250.5 2033.10  5278.8 2043.91  5328.6 2056.98  5335.5 2060.10
#Mann=4,-1,0
  4488.6    0.07       0  5015.1    0.07       0  5019.1    0.07       0
  5055.8    0.16       0
Bank Sta=5015.1,5019.1
Exp/Cntr=0.3,0.1

Type RM Length L Ch R = 1,2399,117,117,117
BEGIN DESCRIPTION:
Elm 91 2398.99
END DESCRIPTION:
XS GIS Cut Line= 3
      1538199.96      6769317.48      1538635.72      6769029.28
      1538824.69      6768772.71
#Sta/Elev= 30
  4470.9 2052.81  4475.0 2050.38  4481.0 2051.03  4496.0 2043.41  4568.3 2034.18
  4748.8 2020.52  4836.1 2016.65  4893.3 2009.72  4950.4 2010.98  4978.5 2006.72
  4978.7 2006.22  4982.5 2006.72  5007.4 2007.16  5115.8 2010.15  5122.0 2013.07
  5130.4 2012.98  5136.6 2019.38  5157.5 2030.29  5165.9 2032.73  5236.9 2044.02
  5251.5 2049.55  5257.7 2046.31  5266.2 2050.88  5272.4 2046.62  5280.6 2054.86
  5287.0 2058.35  5293.2 2055.88  5301.7 2057.66  5307.9 2054.49  5312.0 2054.70
#Mann=4,-1,0
  4470.9    0.07       0  4978.5    0.07       0  4982.5    0.07       0
  5007.4    0.16       0
Bank Sta=4978.5,4982.5
Exp/Cntr=0.3,0.1

Type RM Length L Ch R = 1,2282,121,121,121
BEGIN DESCRIPTION:
Elm 91 2281.76
END DESCRIPTION:
XS GIS Cut Line= 3
      1538316.27      6769374.78      1538734.68      6769088.31
      1539097.52      6768737.62
#Sta/Elev= 30
  4494.8 2049.36  4498.6 2051.36  4513.5 2048.77  4564.3 2034.08  4621.2 2022.52
  4794.5 2013.09  4830.4 2008.28  4844.7 2009.44  4866.3 2006.82  4881.1 2009.55
  4971.9 2003.92  4972.2 2003.42  4975.9 2003.92  5080.1 2006.79  5094.3 2013.94
  5101.2 2020.67  5115.4 2029.44  5129.5 2030.71  5186.1 2022.84  5193.3 2024.89
  5233.5 2013.98  5299.3 2010.09  5405.6 2025.68  5433.6 2024.94  5447.8 2028.21
  5455.0 2032.89  5461.9 2032.05  5469.1 2035.86  5476.1 2032.94  5506.5 2040.85
#Mann=4,-1,0
  4494.8    0.07       0  4971.9    0.07       0  4975.9    0.07       0
  5233.5    0.16       0
Bank Sta=4971.9,4975.9
Exp/Cntr=0.3,0.1

Type RM Length L Ch R = 1,2161,173,173,173
BEGIN DESCRIPTION:
Elm 91 2160.83
END DESCRIPTION:
XS GIS Cut Line= 3
      1538375.35      6769520.57      1538811.07      6769164.70
      1539124.66      6768792.21
#Sta/Elev= 30
  4447.3 2042.44  4456.3 2043.43  4462.7 2040.33  4470.7 2041.80  4477.1 2038.51
  4505.8 2036.53  4584.1 2022.62  4633.6 2019.63  4662.3 2014.53  4705.1 2014.09
  4732.7 2004.97  4753.0 2001.19  4753.2 2000.69  4757.0 2001.19  5067.4 2004.25
  5131.1 2020.09  5137.6 2017.19  5151.9 2016.07  5159.7 2020.43  5174.0 2019.26
  5180.5 2016.07  5188.3 2017.17  5194.8 2013.15  5211.1 2009.28  5237.7 2007.29
  5322.3 2011.90  5350.9 2017.36  5365.2 2023.68  5436.7 2026.79  5496.8 2040.83
#Mann=4,-1,0
  4447.3    0.07       0  4753.0    0.07       0  4757.0    0.07       0
  5211.1    0.16       0
Bank Sta=4753,4757
Exp/Cntr=0.3,0.1

Type RM Length L Ch R = 1,1988,91,91,91
BEGIN DESCRIPTION:
Elm 91 1987.98
END DESCRIPTION:
XS GIS Cut Line= 3
      1538390.90      6769539.73      1538706.91      6769305.33
      1539190.67      6768955.07
#Sta/Elev= 30
  4609.1 2049.95  4620.4 2047.35  4635.0 2048.64  4655.9 2041.07  4776.9 2016.31
  4841.6 2009.73  4850.0 2006.58  4870.8 2005.87  4877.0 2009.81  4891.7 2009.65
  4913.0 2001.96  4933.5 2000.59  4933.8 2000.09  4937.5 2000.59  5042.0 2001.08
  5056.7 2004.59  5086.1 2002.38  5127.9 2005.42  5148.7 2010.78  5249.3 2014.09
  5271.8 2013.47  5299.5 2005.97  5345.6 2005.83  5444.2 2016.92  5450.3 2015.51
  5471.2 2021.95  5536.2 2032.45  5565.6 2041.17  5586.5 2043.01  5599.8 2048.18
#Mann=4,-1,0
  4609.1    0.07       0  4933.5    0.07       0  4937.5    0.07       0
  5345.6    0.16       0
Bank Sta=4933.5,4937.5
Exp/Cntr=0.3,0.1

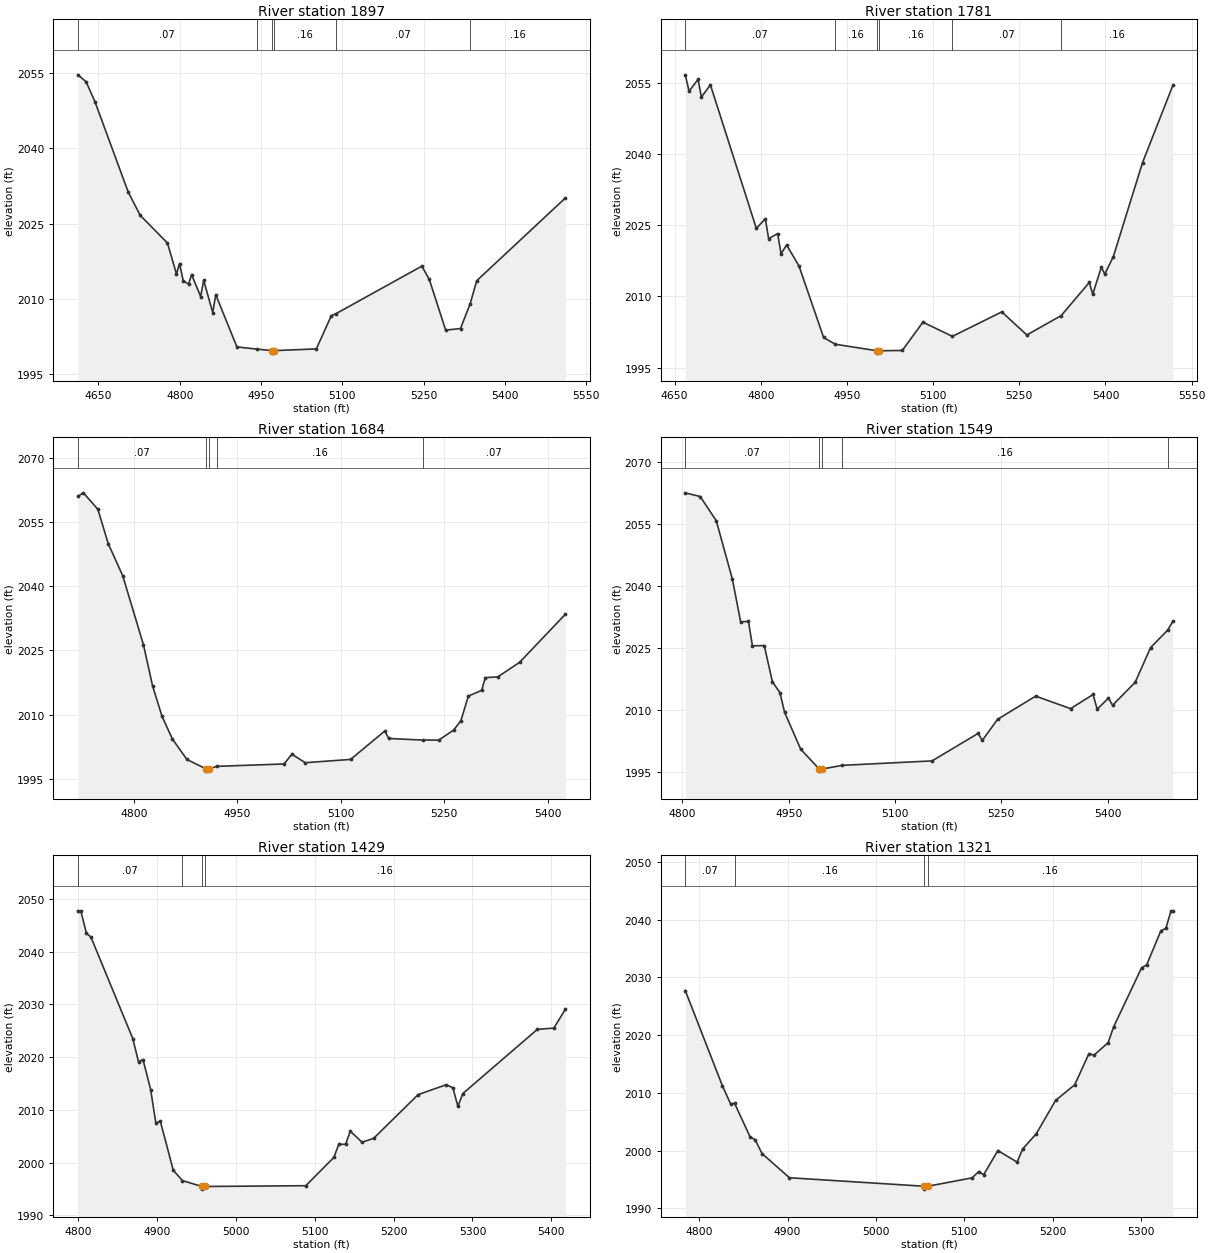
Type RM Length L Ch R = 1,1897,116,116,116
BEGIN DESCRIPTION:
Elm 91 1897.44
END DESCRIPTION:
XS GIS Cut Line= 3
      1538401.37      6769557.05      1538752.04      6769379.98
      1539177.38      6769103.95
#Sta/Elev= 30
  4611.8 2054.58  4627.1 2053.21  4643.4 2049.25  4704.7 2031.29  4727.0 2026.62
  4777.2 2021.13  4793.9 2014.95  4799.5 2017.04  4806.3 2013.65  4816.2 2012.92
  4821.8 2014.84  4838.5 2010.47  4844.1 2013.71  4860.8 2007.27  4866.4 2010.84
  4905.4 2000.45  4941.9 2000.01  4970.3 1999.71  4970.5 1999.21  4974.3 1999.71
  5052.0 2000.05  5079.7 2006.66  5088.3 2007.06  5246.6 2016.51  5260.4 2013.90
  5290.7 2003.79  5318.1 2004.10  5335.9 2009.03  5348.0 2013.61  5511.7 2030.09
#Mann=6,-1,0
  4611.8    0.07       0  4941.9    0.16       0  4970.3    0.07       0
  4974.3    0.16       0  5088.3    0.07       0  5335.9    0.16       0
Bank Sta=4970.3,4974.3
Exp/Cntr=0.3,0.1

Type RM Length L Ch R = 1,1781,97,97,97
BEGIN DESCRIPTION:
Elm 91 1781.1
END DESCRIPTION:
XS GIS Cut Line= 3
      1538522.89      6769645.60      1538802.39      6769480.67
      1539234.64      6769183.83
#Sta/Elev= 30
  4668.4 2056.77  4675.1 2053.30  4690.7 2055.82  4696.5 2052.08  4712.2 2054.65
  4792.2 2024.36  4807.8 2026.42  4813.6 2022.20  4829.3 2023.28  4835.1 2019.01
  4844.9 2020.87  4866.4 2016.44  4909.3 2001.35  4929.7 1999.92  5002.3 1998.55
  5002.6 1998.05  5006.3 1998.55  5046.3 1998.61  5082.1 2004.58  5133.5 2001.59
  5219.5 2006.75  5263.0 2001.88  5323.0 2005.98  5371.8 2012.96  5377.8 2010.48
  5392.7 2016.18  5398.8 2014.73  5413.7 2018.43  5464.5 2038.26  5517.3 2054.55
#Mann=6,-1,0
  4668.4    0.07       0  4929.7    0.16       0  5002.3    0.07       0
  5006.3    0.16       0  5133.5    0.07       0  5323.0    0.16       0
Bank Sta=5002.3,5006.3
Exp/Cntr=0.3,0.1

Type RM Length L Ch R = 1,1684,135,135,135
BEGIN DESCRIPTION:
Elm 91 1684.48
END DESCRIPTION:
XS GIS Cut Line= 3
      1538654.86      6769678.57      1538890.93      6769520.60
      1539286.76      6769371.30
#Sta/Elev= 30
  4718.8 2061.04  4726.9 2061.86  4747.9 2058.01  4762.9 2049.99  4784.0 2042.44
  4814.0 2026.33  4827.3 2016.66  4841.0 2009.56  4856.0 2004.28  4877.0 1999.50
  4905.1 1997.27  4905.3 1996.77  4909.1 1997.27  4920.1 1997.89  5017.9 1998.44
  5029.2 2000.73  5048.7 1998.74  5114.4 1999.51  5164.1 2006.17  5169.5 2004.41
  5219.4 2004.03  5242.3 2004.03  5263.7 2006.36  5274.2 2008.51  5285.1 2014.32
  5304.4 2015.66  5309.8 2018.63  5327.8 2018.81  5359.5 2022.22  5425.9 2033.48
#Mann=5,-1,0
  4718.8    0.07       0  4905.1    0.07       0  4909.1    0.07       0
  4920.1    0.16       0  5219.4    0.07       0
Bank Sta=4905.1,4909.1
Exp/Cntr=0.3,0.1

Type RM Length L Ch R = 1,1549,120,120,120
BEGIN DESCRIPTION:
Elm 91 1549.48
END DESCRIPTION:
XS GIS Cut Line= 3
      1538684.37      6769723.71      1538866.63      6769636.92
      1539291.01      6769399.61
#Sta/Elev= 30
  4804.1 2062.45  4825.2 2061.56  4847.9 2055.70  4870.6 2041.60  4882.3 2031.28
  4893.3 2031.39  4898.9 2025.50  4915.6 2025.55  4927.1 2016.81  4937.7 2014.19
  4944.3 2009.43  4967.0 2000.53  4993.2 1995.73  4993.5 1995.23  4997.2 1995.73
  5025.7 1996.63  5152.4 1997.70  5217.5 2004.36  5223.2 2002.63  5244.9 2007.75
  5298.6 2013.35  5347.8 2010.32  5379.6 2013.74  5385.4 2010.18  5401.3 2012.87
  5407.1 2011.14  5439.0 2016.68  5460.7 2025.06  5484.8 2029.28  5492.2 2031.44
#Mann=5,-1,0
  4804.1    0.07       0  4993.2    0.07       0  4997.2    0.07       0
  5025.7    0.16       0  5484.8    0.07       0
Bank Sta=4993.2,4997.2
Exp/Cntr=0.3,0.1

Type RM Length L Ch R = 1,1429,108,108,108
BEGIN DESCRIPTION:
Elm 91 1429.18
END DESCRIPTION:
XS GIS Cut Line= 3
      1538783.27      6769789.71      1538967.32      6769692.48
      1539301.12      6769453.81
#Sta/Elev= 30
  4799.4 2047.72  4803.2 2047.72  4810.4 2043.43  4816.0 2042.76  4869.2 2023.49
  4876.4 2019.11  4882.1 2019.54  4891.8 2013.86  4898.4 2007.50  4904.1 2007.84
  4920.5 1998.55  4932.1 1996.60  4956.8 1995.48  4957.1 1994.98  4960.8 1995.48
  5088.6 1995.63  5124.3 2001.01  5130.4 2003.48  5139.0 2003.48  5145.1 2005.95
  5159.9 2003.87  5174.6 2004.60  5231.1 2012.89  5266.8 2014.77  5275.2 2014.17
  5281.5 2010.67  5287.7 2013.08  5382.3 2025.26  5403.2 2025.50  5417.9 2029.07
#Mann=4,-1,0
  4799.4    0.07       0  4932.1    0.16       0  4956.8    0.07       0
  4960.8    0.16       0
Bank Sta=4956.8,4960.8
Exp/Cntr=0.3,0.1

Type RM Length L Ch R = 1,1321,127,127,127
BEGIN DESCRIPTION:
Elm 91 1320.83
END DESCRIPTION:
XS GIS Cut Line= 3
      1538847.53      6769867.83      1539041.97      6769768.87
      1539333.68      6769607.39
#Sta/Elev= 30
  4784.3 2027.72  4826.3 2011.23  4835.5 2008.13  4840.2 2008.16  4857.7 2002.36
  4863.3 2001.89  4871.2 1999.48  4902.2 1995.30  5054.6 1993.83  5054.9 1993.33
  5058.6 1993.83  5108.8 1995.28  5116.2 1996.37  5121.9 1995.83  5137.9 2000.01
  5159.7 1998.01  5166.0 2000.29  5181.4 2002.92  5203.2 2008.68  5224.9 2011.41
  5241.0 2016.80  5246.7 2016.53  5262.7 2018.70  5268.8 2021.40  5300.5 2031.65
  5306.2 2032.15  5322.3 2038.05  5328.0 2038.49  5333.8 2041.52  5335.9 2041.52
#Mann=4,-1,0
  4784.3    0.07       0  4840.2    0.16       0  5054.6    0.07       0
  5058.6    0.16       0
Bank Sta=5054.6,5058.6
Exp/Cntr=0.3,0.1

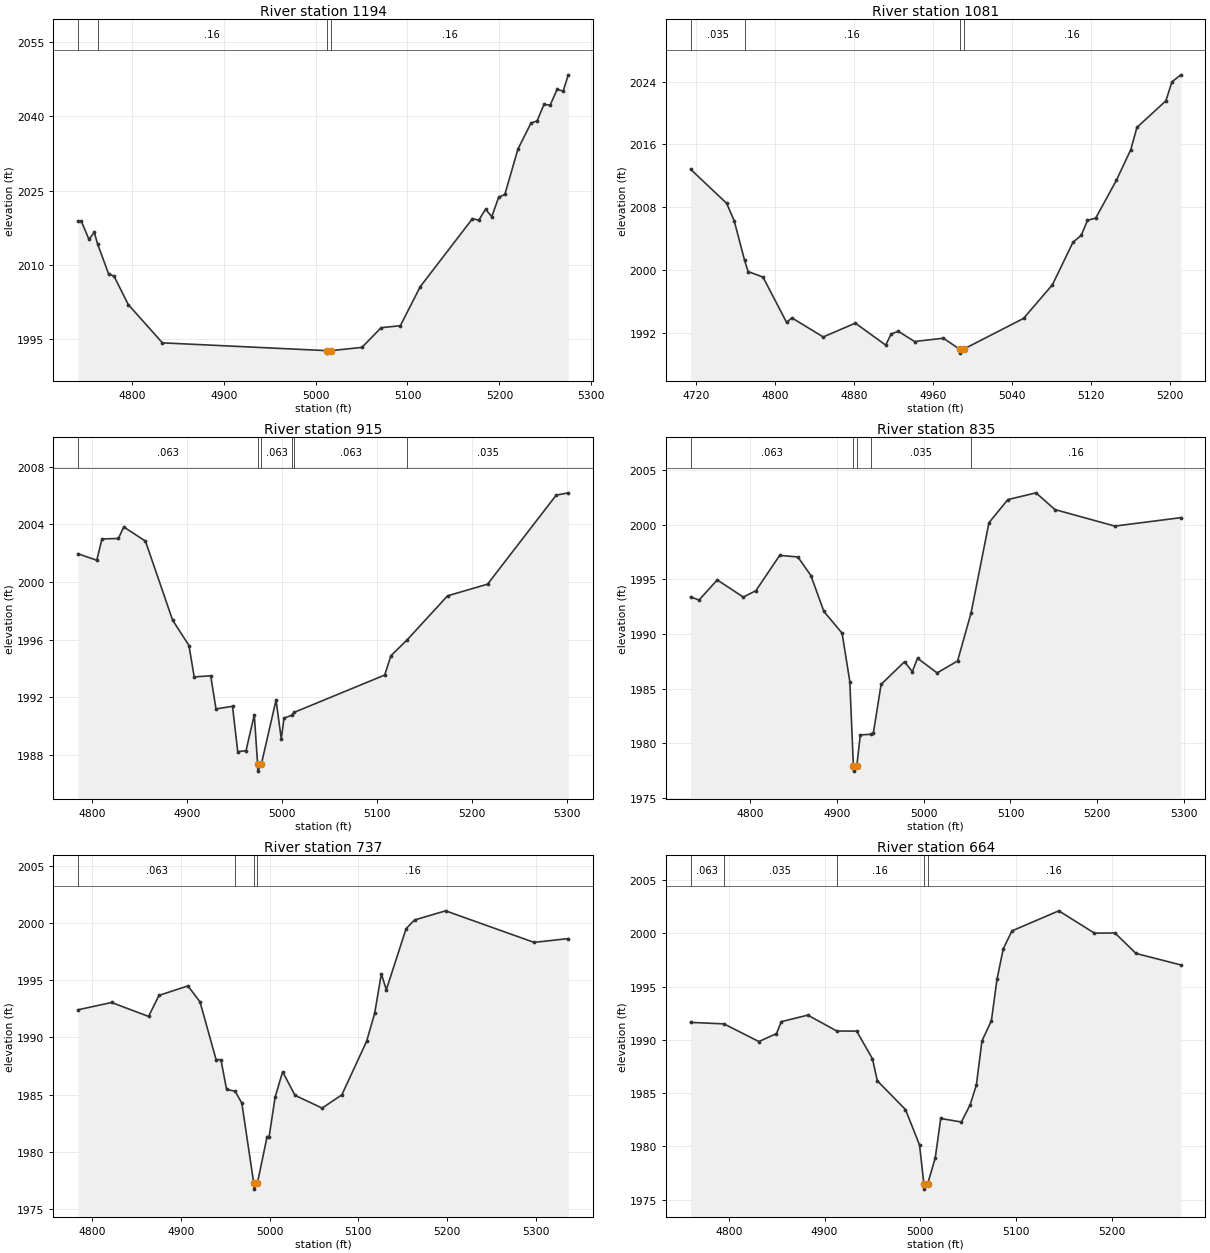
Type RM Length L Ch R = 1,1194,113,113,113
BEGIN DESCRIPTION:
Elm 91 1193.97
END DESCRIPTION:
XS GIS Cut Line= 3
      1538923.89      6769961.59      1539149.61      6769827.90
      1539351.34      6769646.86
#Sta/Elev= 30
  4741.5 2018.85  4745.1 2018.85  4753.5 2015.13  4759.3 2016.56  4762.8 2014.24
  4774.9 2008.13  4780.7 2007.71  4796.3 2001.93  4833.4 1994.20  5012.5 1992.62
  5012.7 1992.12  5016.5 1992.62  5050.4 1993.28  5071.3 1997.26  5092.2 1997.67
  5113.9 2005.57  5170.7 2019.32  5177.5 2019.00  5184.9 2021.23  5191.7 2019.71
  5199.1 2023.63  5205.9 2024.21  5220.1 2033.37  5234.3 2038.64  5241.0 2039.10
  5248.5 2042.43  5255.2 2042.28  5262.7 2045.45  5269.4 2045.14  5274.9 2048.41
#Mann=4,-1,0
  4741.5   0.035       0  4762.8    0.16       0  5012.5    0.07       0
  5016.5    0.16       0
Bank Sta=5012.5,5016.5
Exp/Cntr=0.3,0.1

Type RM Length L Ch R = 1,1081,166,166,166
BEGIN DESCRIPTION:
Elm 91 1081.16
END DESCRIPTION:
XS GIS Cut Line= 3
      1538941.32      6770031.00      1539205.17      6769919.91
      1539373.57      6769794.91
#Sta/Elev= 30
  4714.7 2012.85  4751.2 2008.51  4758.9 2006.27  4769.3 2001.27  4772.9 1999.82
  4788.0 1999.11  4811.8 1993.35  4817.2 1993.92  4848.9 1991.49  4881.4 1993.25
  4912.1 1990.45  4917.6 1991.87  4924.8 1992.21  4941.3 1990.91  4970.5 1991.33
  4986.8 1989.93  4987.0 1989.43  4990.8 1989.93  5051.5 1993.85  5080.7 1998.13
  5101.5 2003.54  5109.9 2004.43  5116.2 2006.34  5124.6 2006.64  5145.4 2011.43
  5160.0 2015.34  5166.2 2018.17  5195.5 2021.56  5201.7 2023.99  5210.7 2024.87
#Mann=4,-1,0
  4714.7   0.035       0  4769.3    0.16       0  4986.8    0.07       0
  4990.8    0.16       0
Bank Sta=4986.8,4990.8
Exp/Cntr=0.3,0.1

Type RM Length L Ch R = 1,915,80,80,80
BEGIN DESCRIPTION:
Elm 91 915.45
END DESCRIPTION:
XS GIS Cut Line= 3
      1538984.70      6770152.54      1539182.60      6770060.53
      1539430.45      6769895.88
#Sta/Elev= 30
  4785.5 2001.96  4805.3 2001.51  4810.8 2002.99  4828.1 2003.02  4833.7 2003.82
  4856.5 2002.84  4885.1 1997.35  4902.3 1995.59  4907.8 1993.41  4925.2 1993.49
  4930.7 1991.19  4948.1 1991.37  4953.6 1988.22  4962.3 1988.29  4971.0 1990.77
  4974.5 1987.37  4974.7 1986.87  4978.5 1987.37  4993.9 1991.81  4999.4 1989.10
  5002.3 1990.55  5010.5 1990.75  5012.9 1990.95  5108.2 1993.54  5114.7 1994.88
  5131.6 1995.97  5174.3 1999.04  5216.4 1999.85  5288.6 2006.03  5301.3 2006.19
#Mann=6,-1,0
  4785.5   0.063       0  4974.5   0.063       0  4978.5   0.063       0
  5010.5   0.035       0  5012.9   0.063       0  5131.6   0.035       0
Bank Sta=4974.5,4978.5
Exp/Cntr=0.3,0.1

Type RM Length L Ch R = 1,835,98,98,98
BEGIN DESCRIPTION:
Elm 91 835.07
END DESCRIPTION:
XS GIS Cut Line= 3
      1539012.49      6770268.85      1539234.68      6770119.56
      1539508.60      6770002.42
#Sta/Elev= 30
  4731.0 1993.40  4740.8 1993.11  4761.8 1994.95  4791.8 1993.38  4806.3 1993.96
  4833.8 1997.19  4854.8 1997.05  4869.8 1995.35  4884.8 1992.07  4905.8 1990.08
  4914.7 1985.66  4918.8 1977.97  4919.0 1977.47  4922.8 1977.97  4926.8 1980.78
  4939.5 1980.84  4941.8 1980.92  4950.8 1985.40  4977.8 1987.47  4986.8 1986.56
  4992.8 1987.79  5015.4 1986.45  5039.0 1987.54  5054.6 1991.94  5075.2 2000.18
  5097.0 2002.29  5129.5 2002.91  5151.3 2001.38  5220.4 1999.87  5296.6 2000.64
#Mann=5,-1,0
  4731.0   0.063       0  4918.8   0.035       0  4922.8   0.063       0
  4939.5   0.035       0  5054.6    0.16       0
Bank Sta=4918.8,4922.8
Exp/Cntr=0.3,0.1

Type RM Length L Ch R = 1,737,73,73,73
BEGIN DESCRIPTION:
Elm 91 736.64
END DESCRIPTION:
XS GIS Cut Line= 3
      1539021.14      6770286.23      1539219.06      6770201.16
      1539519.41      6770048.38
#Sta/Elev= 30
  4784.0 1992.42  4821.9 1993.06  4863.6 1991.84  4875.3 1993.68  4907.9 1994.51
  4921.5 1993.12  4939.6 1988.07  4945.1 1988.05  4951.5 1985.45  4961.0 1985.30
  4968.6 1984.27  4982.1 1977.23  4982.4 1976.73  4986.1 1977.23  4997.1 1981.32
  4999.4 1981.32  5006.1 1984.76  5014.6 1987.00  5028.5 1984.94  5059.1 1983.82
  5081.3 1984.98  5109.2 1989.66  5118.3 1992.12  5125.8 1995.57  5131.4 1994.17
  5153.7 1999.52  5163.2 2000.28  5198.2 2001.08  5297.8 1998.32  5336.4 1998.65
#Mann=4,-1,0
  4784.0   0.063       0  4961.0    0.16       0  4982.1    0.07       0
  4986.1    0.16       0
Bank Sta=4982.1,4986.1
Exp/Cntr=0.3,0.1

Type RM Length L Ch R = 1,664,50,50,50
BEGIN DESCRIPTION:
Elm 91 664.04
END DESCRIPTION:
XS GIS Cut Line= 3
      1539035.06      6770301.85      1539269.41      6770253.24
      1539505.53      6770116.08
#Sta/Elev= 30
  4759.9 1991.64  4794.8 1991.50  4831.3 1989.84  4849.7 1990.59  4854.8 1991.71
  4882.4 1992.32  4912.7 1990.83  4933.5 1990.82  4950.0 1988.22  4955.1 1986.15
  4984.5 1983.46  4999.2 1980.13  5003.7 1976.49  5004.0 1975.99  5007.7 1976.49
  5015.6 1978.92  5021.3 1982.62  5042.9 1982.29  5052.0 1983.89  5058.6 1985.77
  5064.4 1989.90  5074.3 1991.80  5080.1 1995.67  5086.7 1998.56  5095.8 2000.23
  5144.7 2002.11  5181.9 2000.02  5203.4 2000.03  5225.4 1998.11  5272.3 1997.03
#Mann=5,-1,0
  4759.9   0.063       0  4794.8   0.035       0  4912.7    0.16       0
  5003.7    0.07       0  5007.7    0.16       0
Bank Sta=5003.7,5007.7
Exp/Cntr=0.3,0.1