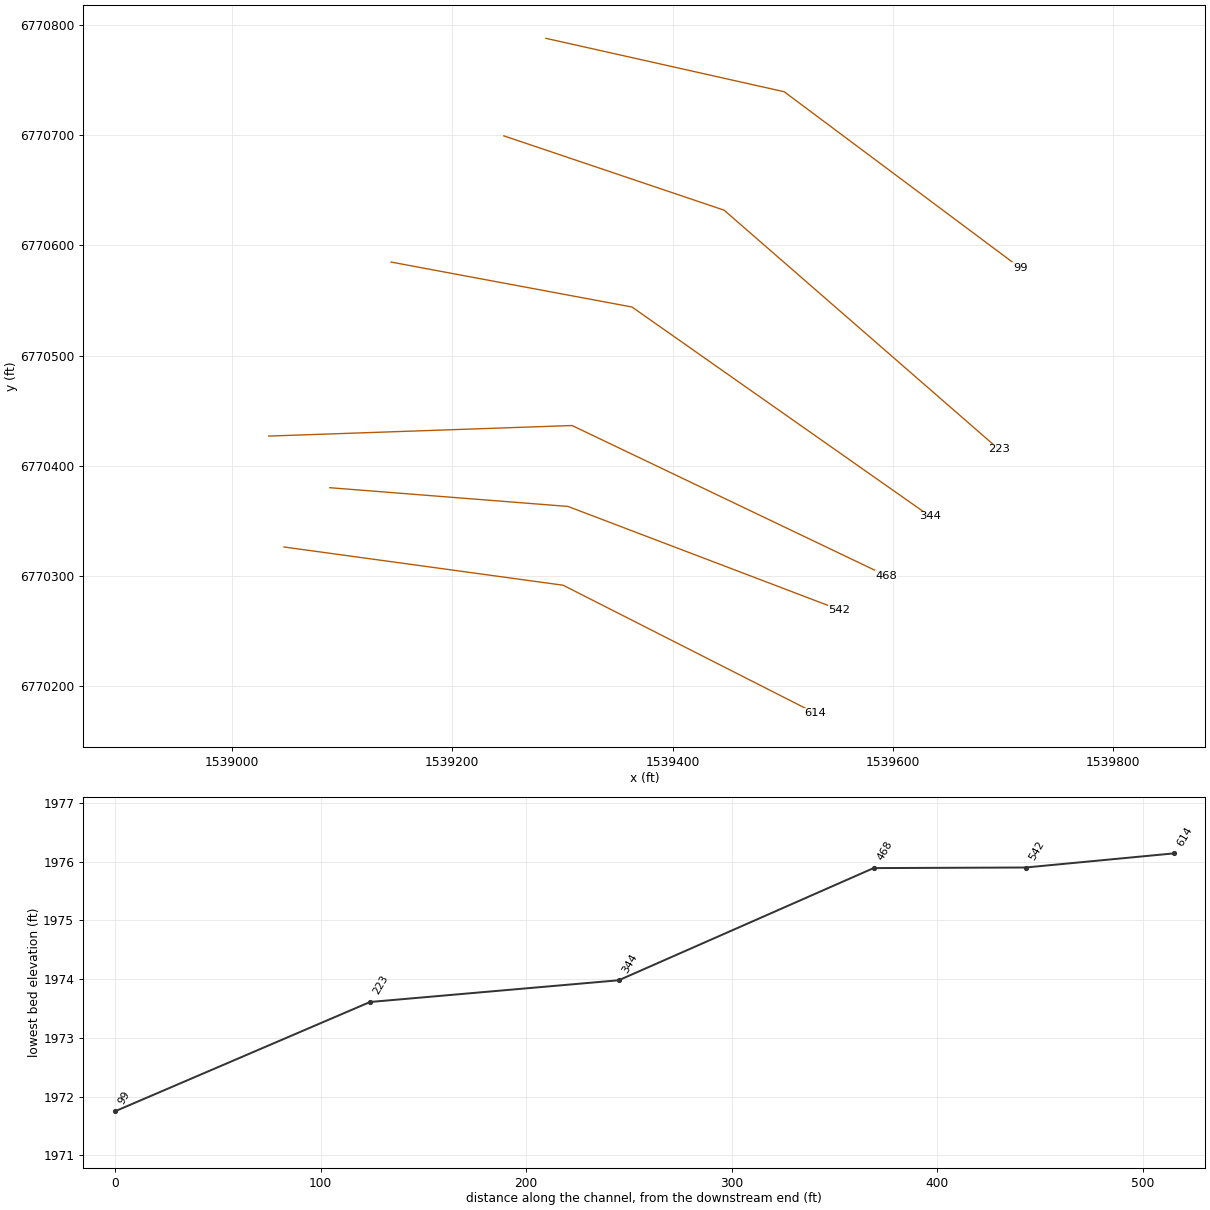
HEC-RAS study Elm 91.prj: Elm 91 Base Level Engineering

--- Elm 91.g01 (geometry) --- (continued)

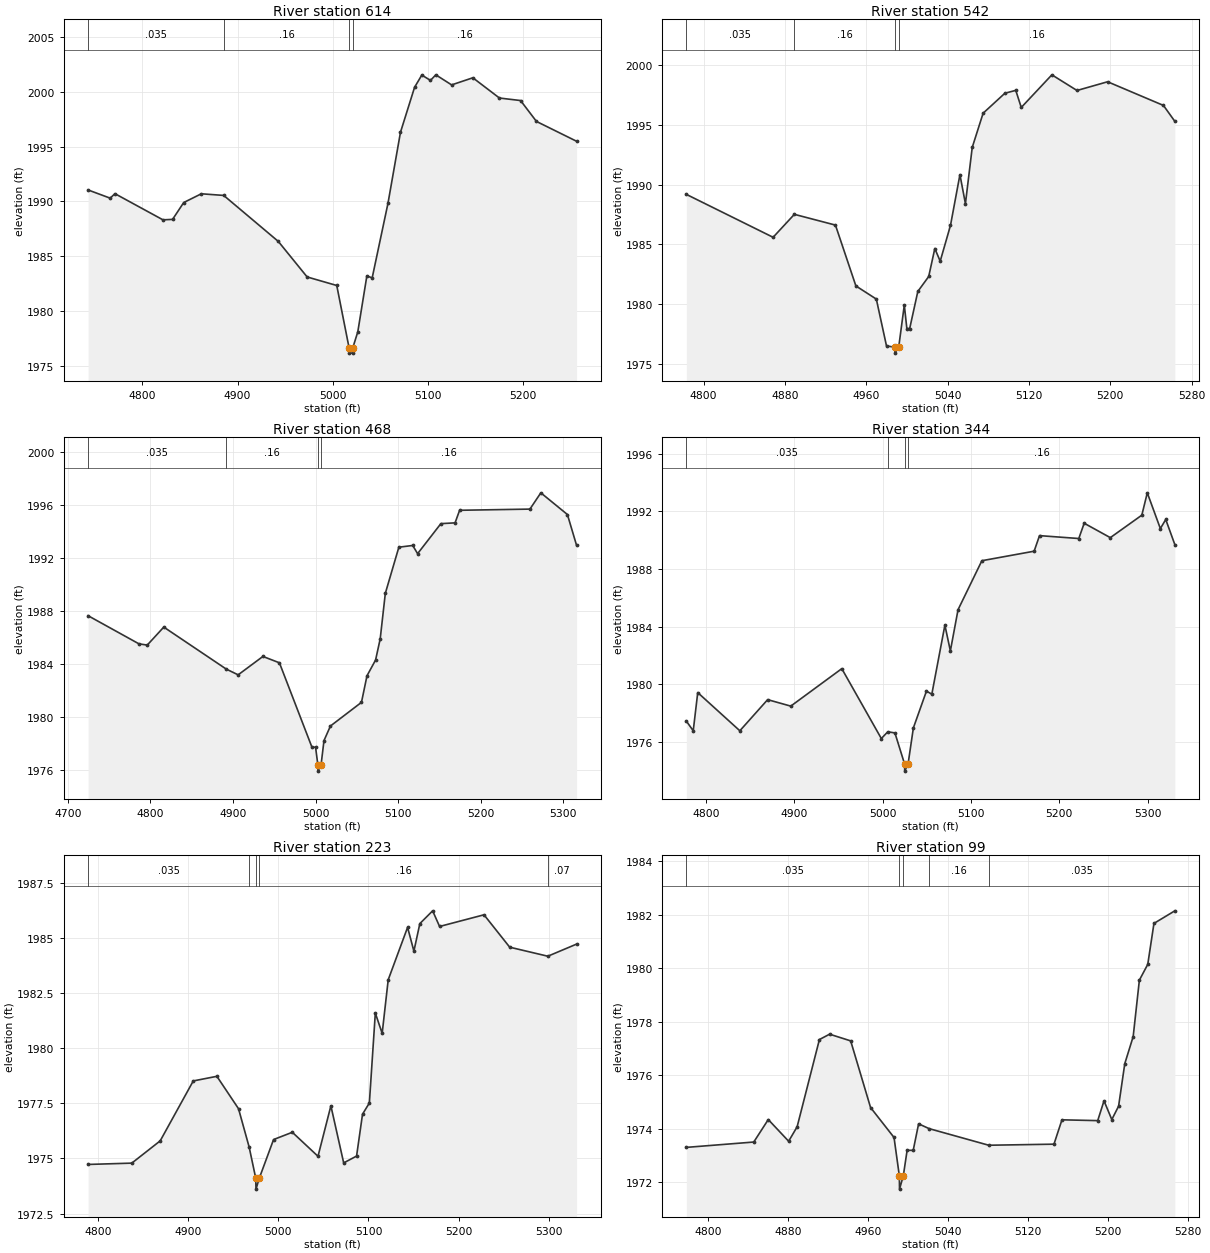
Type RM Length L Ch R = 1,614,72,72,72
BEGIN DESCRIPTION:
Elm 91 614.22
END DESCRIPTION:
XS GIS Cut Line= 3
      1539047.16      6770326.16      1539300.66      6770291.44
      1539529.86      6770175.10
#Sta/Elev= 30
  4743.0 1991.05  4766.2 1990.30  4771.2 1990.71  4821.6 1988.32  4831.7 1988.36
  4843.4 1989.90  4861.9 1990.70  4885.4 1990.55  4942.7 1986.35  4973.0 1983.10
  5004.1 1982.32  5017.0 1976.64  5017.3 1976.14  5020.8 1976.14  5021.0 1976.64
  5026.2 1978.09  5035.7 1983.19  5041.3 1983.02  5057.9 1989.84  5071.0 1996.32
  5085.8 2000.43  5093.4 2001.55  5102.5 2001.06  5108.1 2001.57  5124.7 2000.65
  5147.0 2001.30  5174.9 1999.45  5197.1 1999.22  5213.8 1997.31  5255.9 1995.50
#Mann=4,-1,0
  4743.0   0.035       0  4885.4    0.16       0  5017.0    0.07       0
  5021.0    0.16       0
Bank Sta=5017,5021
Exp/Cntr=0.3,0.1

Type RM Length L Ch R = 1,542,74,74,74
BEGIN DESCRIPTION:
Elm 91 541.867
END DESCRIPTION:
XS GIS Cut Line= 3
      1539088.81      6770379.98      1539305.04      6770362.98
      1539551.22      6770269.31
#Sta/Elev= 30
  4783.1 1989.18  4868.4 1985.59  4889.3 1987.51  4929.7 1986.61  4949.8 1981.52
  4969.9 1980.42  4979.9 1976.50  4987.9 1976.40  4988.2 1975.90  4991.9 1976.40
  4997.4 1979.92  4999.9 1977.96  5002.7 1977.96  5010.7 1981.06  5021.4 1982.31
  5027.4 1984.65  5032.7 1983.59  5042.8 1986.58  5052.1 1990.83  5057.5 1988.40
  5064.2 1993.11  5074.9 1995.97  5096.3 1997.64  5107.0 1997.88  5112.4 1996.45
  5142.5 1999.18  5167.2 1997.87  5197.3 1998.60  5252.2 1996.62  5263.4 1995.29
#Mann=4,-1,0
  4783.1   0.035       0  4889.3    0.16       0  4987.9    0.07       0
  4991.9    0.16       0
Bank Sta=4987.9,4991.9
Exp/Cntr=0.3,0.1

Type RM Length L Ch R = 1,468,124,124,124
BEGIN DESCRIPTION:
Elm 91 3941
END DESCRIPTION:
XS GIS Cut Line= 3
      1539033.32      6770426.86      1539308.76      6770436.44
      1539594.06      6770300.12
#Sta/Elev= 30
  4724.4 1987.64  4786.1 1985.51  4796.1 1985.42  4816.1 1986.78  4891.9 1983.60
  4906.2 1983.17  4936.2 1984.56  4956.2 1984.08  4995.6 1977.70  5000.0 1977.70
  5002.7 1976.39  5002.9 1975.89  5006.7 1976.39  5010.2 1978.20  5018.0 1979.30
  5055.6 1981.09  5062.3 1983.10  5072.7 1984.29  5078.3 1985.89  5084.5 1989.33
  5100.9 1992.82  5117.7 1992.95  5123.6 1992.33  5151.8 1994.60  5169.0 1994.66
  5174.5 1995.61  5259.7 1995.70  5272.9 1996.93  5305.1 1995.29  5316.2 1992.96
#Mann=4,-1,0
  4724.4   0.035       0  4891.9    0.16       0  5002.7    0.07       0
  5006.7    0.16       0
Bank Sta=5002.7,5006.7
Exp/Cntr=0.3,0.1

Type RM Length L Ch R = 1,344,121,121,121
BEGIN DESCRIPTION:
Elm 91 3940
END DESCRIPTION:
XS GIS Cut Line= 3
      1539144.43      6770584.84      1539363.16      6770544.05
      1539633.99      6770353.94
#Sta/Elev= 30
  4777.5 1977.45  4785.3 1976.78  4790.4 1979.43  4838.1 1976.78  4869.6 1978.94
  4895.8 1978.49  4953.6 1981.09  4998.4 1976.24  5005.7 1976.71  5013.8 1976.63
  5024.7 1974.48  5024.9 1973.98  5028.7 1974.48  5034.7 1976.98  5049.5 1979.53
  5055.6 1979.32  5070.4 1984.11  5076.6 1982.32  5085.3 1985.18  5112.3 1988.58
  5171.5 1989.24  5177.6 1990.32  5222.1 1990.12  5228.2 1991.18  5257.8 1990.18
  5293.5 1991.74  5299.7 1993.29  5314.5 1990.81  5320.6 1991.44  5330.9 1989.70
#Mann=4,-1,0
  4777.5   0.035       0  5005.7    0.16       0  5024.7   0.035       0
  5028.7    0.16       0
Bank Sta=5024.7,5028.7
Exp/Cntr=0.3,0.1

Type RM Length L Ch R = 1,223,124,124,124
BEGIN DESCRIPTION:
Elm 91 3939
END DESCRIPTION:
XS GIS Cut Line= 3
      1539246.82      6770699.43      1539446.84      6770631.95
      1539696.46      6770414.73
#Sta/Elev= 30
  4788.9 1974.73  4837.4 1974.79  4868.9 1975.80  4905.6 1978.52  4931.8 1978.73
  4955.8 1977.26  4967.6 1975.52  4974.9 1974.11  4975.2 1973.61  4978.9 1974.11
  4994.7 1975.86  5015.5 1976.19  5044.0 1975.10  5058.3 1977.39  5072.5 1974.80
  5086.8 1975.11  5093.4 1977.01  5101.0 1977.52  5107.6 1981.60  5115.2 1980.68
  5121.9 1983.11  5143.4 1985.49  5150.4 1984.41  5157.0 1985.66  5171.2 1986.24
  5178.9 1985.53  5228.2 1986.06  5256.7 1984.59  5299.0 1984.18  5330.9 1984.73
#Mann=5,-1,0
  4788.9   0.035       0  4967.6    0.16       0  4974.9    0.07       0
  4978.9    0.16       0  5299.0    0.07       0
Bank Sta=4974.9,4978.9
Exp/Cntr=0.3,0.1

Type RM Length L Ch R = 1,99,0,0,0
BEGIN DESCRIPTION:
Elm 91 3937
END DESCRIPTION:
XS GIS Cut Line= 3
      1539285.03      6770787.97      1539501.37      6770739.50
      1539715.59      6770579.63
#Sta/Elev= 30
  4778.3 1973.31  4845.8 1973.51  4860.3 1974.35  4880.7 1973.54  4889.2 1974.08
  4911.5 1977.34  4921.7 1977.54  4942.8 1977.29  4962.7 1974.80  4986.2 1973.68
  4991.5 1972.25  4991.7 1971.75  4995.5 1972.25  4999.3 1973.20  5005.4 1973.20
  5010.8 1974.19  5021.4 1974.01  5081.0 1973.39  5146.3 1973.43  5154.3 1974.34
  5190.1 1974.31  5196.4 1975.05  5204.2 1974.35  5211.0 1974.85  5217.2 1976.44
  5225.6 1977.45  5231.8 1979.56  5240.2 1980.15  5246.4 1981.68  5267.3 1982.15
#Mann=5,-1,0
  4778.3   0.035       0  4991.5   0.035       0  4995.5   0.035       0
  5021.4    0.16       0  5081.0   0.035       0
Bank Sta=4991.5,4995.5
Exp/Cntr=0.3,0.1

Chan Stop Cuts=-1