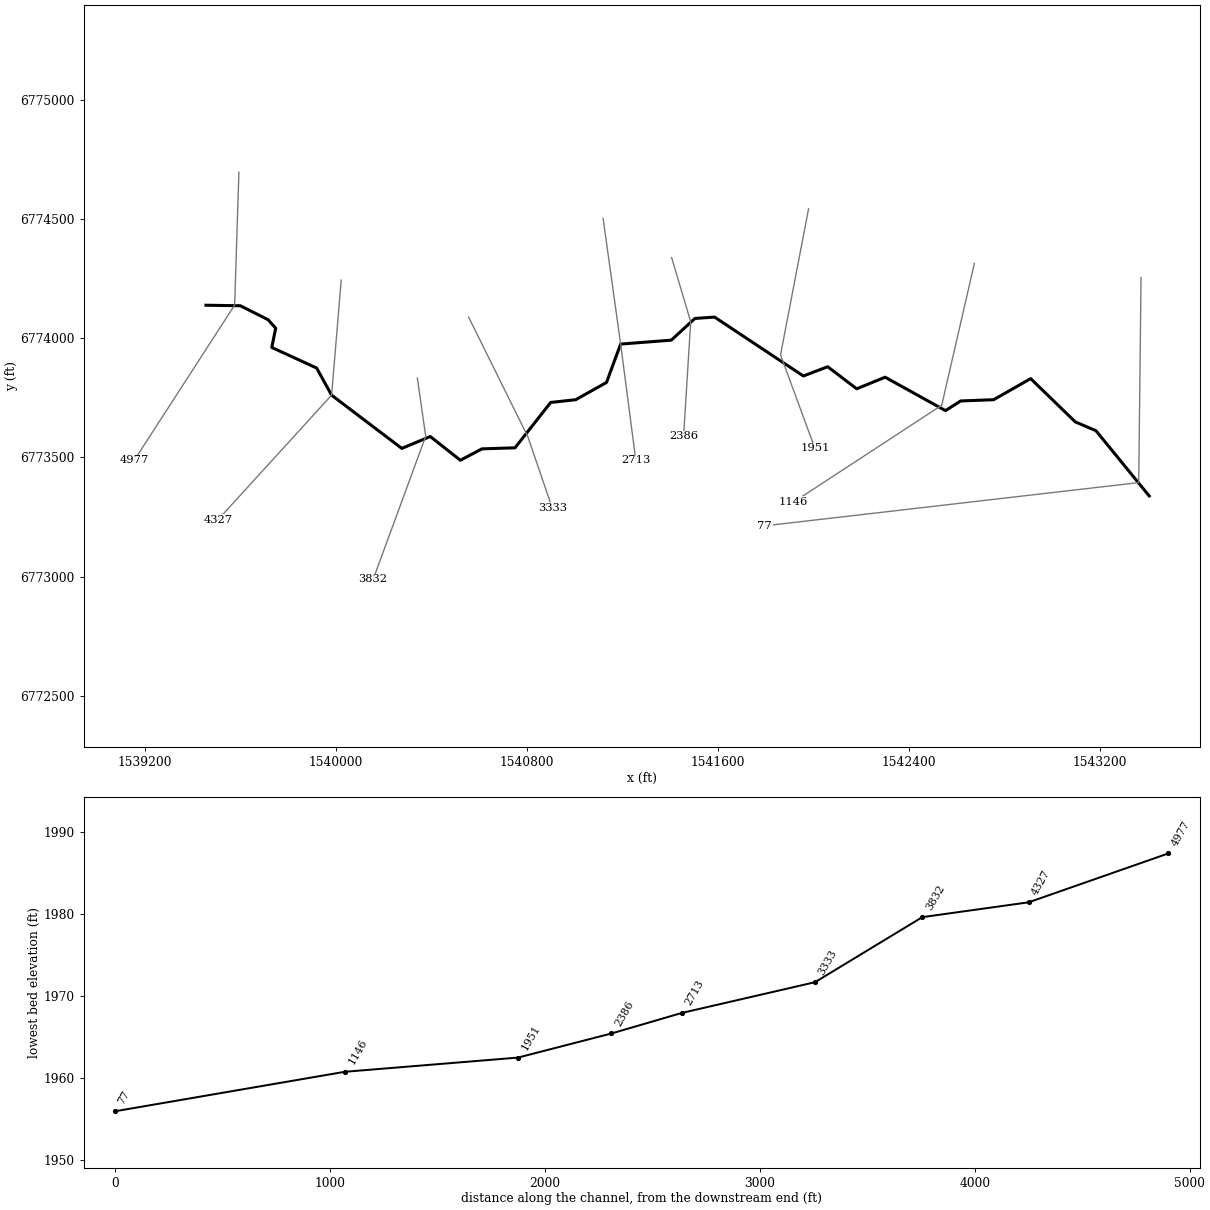
--- Elm 92.prj (project) ---

Proj Title=Elm 92 Base Level Engineering
Current Plan=p01
Default Exp/Contr=0.3,0.1
English Units
Geom File=g01
Flow File=f01
Plan File=p01
BEGIN DESCRIPTION:
Elm 92
END DESCRIPTION:

--- Elm 92.p01 (plan) ---

Plan Title=Multiple Run
Short Identifier=Multiple
Geom File=g01
Flow File=f01
Subcritical Flow
K Sum by GR= 0
Std Step Tol= 0.01
Critical Tol= 0.01
Num of Std Step Trials= 20
Max Error Tol= 0.3
Flow Tol Ratio= 0.001
Split Flow NTrial= 30
Split Flow Tol= 0.02
Split Flow Ratio= 0.02
Log Output Level= 0
Friction Slope Method= 1
Unsteady Friction Slope Method= 2
Unsteady Bridges Friction Slope Method= 1
Parabolic Critical Depth
Global Vel Dist=  1 , 1 , 1
Global Log Level= 0
CheckData=True
Encroach Param= -1, 0, 0, 0
BEGIN DESCRIPTION:
Multiple Run
END DESCRIPTION:

--- Elm 92.f01 (steady flow) ---

Flow Title=Multiple
Number of Profiles=7
Profile Names=10-year,25-year,50-year,1pct_min,100-year,1pct_plu,500-year
River Rch & RM= Elm 92,Reach-1,4977
     163     222     270     204     328     451     487
River Rch & RM= Elm 92,Reach-1,2713
     282     397     493     381     611     841     948
Boundary for River Rch & Prof#=Elm 92,Reach-1,1
Up Type=0
Dn Type=3
Dn Slope=0.005
Boundary for River Rch & Prof#=Elm 92,Reach-1,2
Up Type=0
Dn Type=3
Dn Slope=0.005
Boundary for River Rch & Prof#=Elm 92,Reach-1,3
Up Type=0
Dn Type=3
Dn Slope=0.005
Boundary for River Rch & Prof#=Elm 92,Reach-1,4
Up Type=0
Dn Type=3
Dn Slope=0.005
Boundary for River Rch & Prof#=Elm 92,Reach-1,5
Up Type=0
Dn Type=3
Dn Slope=0.005
Boundary for River Rch & Prof#=Elm 92,Reach-1,6
Up Type=0
Dn Type=3
Dn Slope=0.005
Boundary for River Rch & Prof#=Elm 92,Reach-1,7
Up Type=0
Dn Type=3
Dn Slope=0.005

--- Elm 92.g01 (geometry) ---

Geom Title=Existing Conditions

River Reach=Elm 92,Reach-1
Reach XY= 30
      1539455.00      6774138.00      1539599.09      6774135.81
      1539715.39      6774077.24      1539747.10      6774041.57
      1539730.64      6773961.01      1539918.56      6773874.52
      1539981.17      6773760.87      1540275.13      6773537.61
      1540394.37      6773587.39      1540520.34      6773487.96
      1540610.93      6773535.70      1540749.15      6773540.06
      1540898.55      6773730.26      1541003.41      6773741.83
      1541132.29      6773814.06      1541191.50      6773975.08
      1541403.53      6773991.55      1541502.58      6774082.59
      1541584.94      6774088.21      1541956.65      6773841.17
      1542058.40      6773880.16      1542179.96      6773787.52
      1542298.89      6773836.20      1542551.68      6773696.04
      1542615.44      6773736.60      1542753.44      6773741.76
      1542908.41      6773830.23      1543095.32      6773648.78
      1543181.82      6773611.70      1543405.00      6773338.00

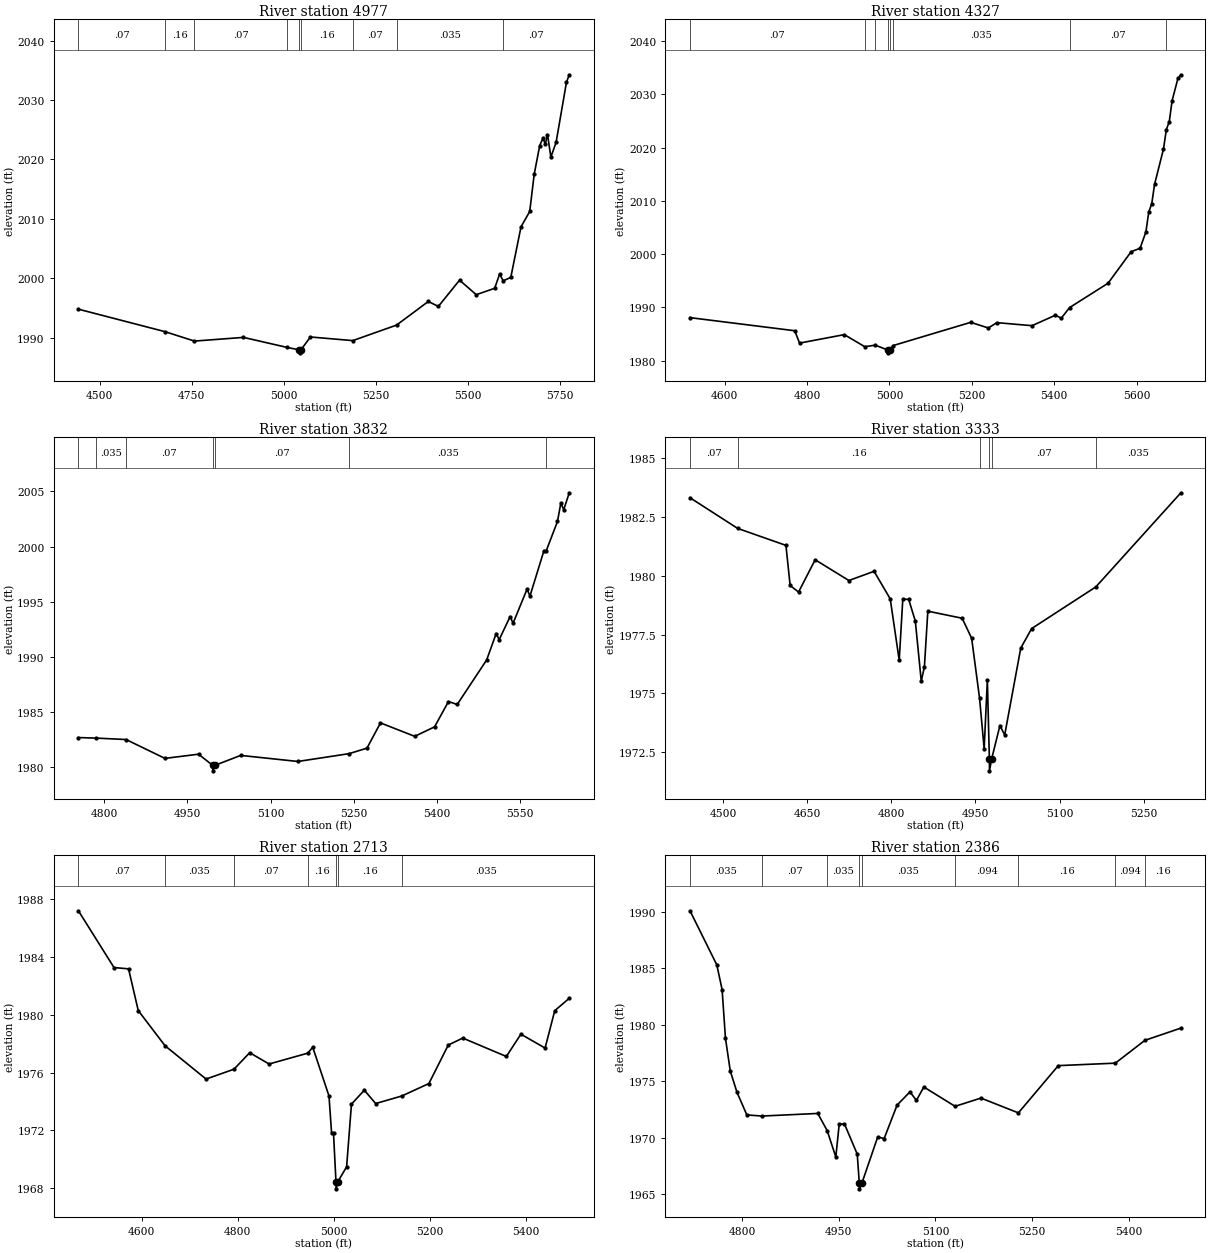
Type RM Length L Ch R = 1,4977,650,650,650
BEGIN DESCRIPTION:
383
END DESCRIPTION:
XS GIS Cut Line= 3
      1539593.05      6774695.66      1539575.18      6774138.44
      1539154.98      6773487.96
#Sta/Elev= 30
  4442.5 1994.77  4677.3 1990.99  4757.3 1989.40  4890.4 1990.02  5009.6 1988.32
  5042.3 1987.92  5042.6 1987.42  5046.3 1987.92  5072.0 1990.09  5187.0 1989.48
  5305.7 1992.09  5392.0 1996.07  5419.1 1995.23  5476.7 1999.66  5522.0 1997.21
  5572.0 1998.29  5585.3 2000.68  5595.2 1999.55  5615.7 2000.12  5643.4 2008.63
  5667.1 2011.23  5679.1 2017.45  5694.2 2022.32  5702.9 2023.55  5709.4 2022.57
  5715.3 2024.18  5724.5 2020.39  5738.6 2022.85  5766.8 2032.99  5774.4 2034.24
#Mann=9,-1,0
  4442.5    0.07       0  4677.3    0.16       0  4757.3    0.07       0
  5009.6    0.16       0  5042.3    0.07       0  5046.3    0.16       0
  5187.0    0.07       0  5305.7   0.035       0  5595.2    0.07       0
Bank Sta=5042.3,5046.3
Exp/Cntr=0.3,0.1

Type RM Length L Ch R = 1,4327,495,495,495
BEGIN DESCRIPTION:
382
END DESCRIPTION:
XS GIS Cut Line= 3
      1540021.40      6774242.99      1539981.17      6773760.87
      1539505.00      6773238.00
#Sta/Elev= 30
  4516.2 1988.07  4770.3 1985.61  4782.1 1983.29  4890.6 1984.88  4940.3 1982.61
  4965.9 1982.90  4996.9 1981.96  4997.2 1981.46  5000.9 1981.96  5009.2 1982.83
  5197.4 1987.19  5240.0 1986.13  5260.9 1987.13  5346.0 1986.56  5402.8 1988.53
  5417.0 1987.96  5437.0 1989.95  5530.5 1994.53  5586.6 2000.46  5608.2 2001.09
  5622.4 2004.18  5629.2 2007.88  5636.6 2009.50  5643.3 2013.08  5665.0 2019.74
  5672.0 2023.40  5679.1 2024.89  5685.9 2028.80  5700.1 2033.02  5707.2 2033.68
#Mann=8,-1,0
  4516.2    0.07       0  4940.3   0.035       0  4965.9    0.07       0
  4996.9    0.07       0  5000.9    0.07       0  5009.2   0.035       0
  5437.0    0.07       0  5672.0   0.033       0
Bank Sta=4996.9,5000.9
Exp/Cntr=0.3,0.1

Type RM Length L Ch R = 1,3832,499,499,499
BEGIN DESCRIPTION:
381
END DESCRIPTION:
XS GIS Cut Line= 3
      1540340.20      6773832.75      1540375.20      6773588.34
      1540154.98      6772987.96
#Sta/Elev= 30
  4753.1 1982.67  4785.3 1982.62  4839.2 1982.49  4909.4 1980.78  4970.0 1981.16
  4995.6 1980.15  4995.9 1979.65  4999.6 1980.15  5046.2 1981.05  5149.5 1980.50
  5242.0 1981.21  5274.2 1981.71  5298.6 1984.00  5360.4 1982.78  5396.2 1983.64
  5421.4 1985.94  5437.1 1985.67  5490.3 1989.71  5507.5 1992.11  5512.9 1991.55
  5532.7 1993.65  5538.0 1993.04  5563.2 1996.13  5568.5 1995.51  5593.7 1999.62
  5597.7 1999.59  5618.2 2002.28  5624.2 2003.94  5629.5 2003.35  5639.5 2004.88
#Mann=7,-1,0
  4753.1    0.07       0  4785.3   0.035       0  4839.2    0.07       0
  4995.6    0.07       0  4999.6    0.07       0  5242.0   0.035       0
  5597.7    0.07       0
Bank Sta=4995.6,4999.6
Exp/Cntr=0.3,0.1

Type RM Length L Ch R = 1,3333,620,620,620
BEGIN DESCRIPTION:
380
END DESCRIPTION:
XS GIS Cut Line= 3
      1540555.02      6774087.96      1540802.72      6773587.06
      1540905.01      6773287.97
#Sta/Elev= 30
  4441.2 1983.30  4526.1 1982.00  4612.2 1981.28  4619.7 1979.58  4634.7 1979.30
  4664.3 1980.67  4724.4 1979.79  4769.3 1980.18  4798.1 1979.01  4814.1 1976.41
  4820.5 1979.00  4831.0 1978.99  4842.8 1978.07  4853.4 1975.52  4859.0 1976.13
  4865.1 1978.49  4926.3 1978.19  4943.2 1977.34  4957.3 1974.80  4965.5 1972.66
  4971.2 1975.57  4974.8 1972.22  4975.0 1971.72  4978.8 1972.22  4993.6 1973.64
  5002.1 1973.24  5030.7 1976.92  5050.0 1977.75  5164.6 1979.52  5316.1 1983.51
#Mann=6,-1,0
  4441.2    0.07       0  4526.1    0.16       0  4957.3    0.07       0
  4974.8    0.07       0  4978.8    0.07       0  5164.6   0.035       0
Bank Sta=4974.8,4978.8
Exp/Cntr=0.3,0.1

Type RM Length L Ch R = 1,2713,327,327,327
BEGIN DESCRIPTION:
379
END DESCRIPTION:
XS GIS Cut Line= 3
      1541118.10      6774501.49      1541191.50      6773975.08
      1541255.00      6773488.00
#Sta/Elev= 30
  4468.5 1987.17  4542.7 1983.25  4573.0 1983.16  4593.2 1980.28  4649.0 1977.85
  4734.5 1975.55  4792.6 1976.23  4825.4 1977.37  4865.8 1976.59  4946.5 1977.34
  4956.7 1977.75  4990.6 1974.38  4996.0 1971.80  5000.0 1971.80  5005.1 1968.47
  5005.4 1967.97  5009.1 1968.47  5027.3 1969.49  5037.4 1973.82  5064.2 1974.78
  5087.8 1973.86  5142.2 1974.38  5198.7 1975.24  5239.1 1977.90  5269.3 1978.38
  5360.1 1977.11  5390.4 1978.65  5440.8 1977.69  5460.9 1980.27  5491.2 1981.13
#Mann=7,-1,0
  4468.5    0.07       0  4649.0   0.035       0  4792.6    0.07       0
  4946.5    0.16       0  5005.1    0.07       0  5009.1    0.16       0
  5142.2   0.035       0
Bank Sta=5005.1,5009.1
Exp/Cntr=0.3,0.1

Type RM Length L Ch R = 1,2386,435,435,435
BEGIN DESCRIPTION:
378
END DESCRIPTION:
XS GIS Cut Line= 3
      1541405.00      6774337.99      1541484.86      6774068.37
      1541455.00      6773588.00
#Sta/Elev= 30
  4718.8 1990.07  4760.5 1985.28  4768.7 1983.09  4773.9 1978.79  4781.4 1975.89
  4791.8 1974.01  4807.1 1972.01  4830.6 1971.91  4917.3 1972.14  4931.9 1970.62
  4945.3 1968.29  4950.6 1971.19  4958.7 1971.22  4978.6 1968.54  4981.8 1965.97
  4982.1 1965.47  4985.8 1965.97  5010.4 1970.06  5020.4 1969.92  5040.5 1972.88
  5060.5 1974.05  5070.5 1973.29  5082.0 1974.48  5130.6 1972.77  5170.7 1973.50
  5228.9 1972.19  5290.9 1976.37  5379.5 1976.59  5425.5 1978.61  5481.3 1979.69
#Mann=9,-1,0
  4718.8   0.035       0  4830.6    0.07       0  4931.9   0.035       0
  4981.8   0.035       0  4985.8   0.035       0  5130.6   0.094       0
  5228.9    0.16       0  5379.5   0.094       0  5425.5    0.16       0
Bank Sta=4981.8,4985.8
Exp/Cntr=0.3,0.1

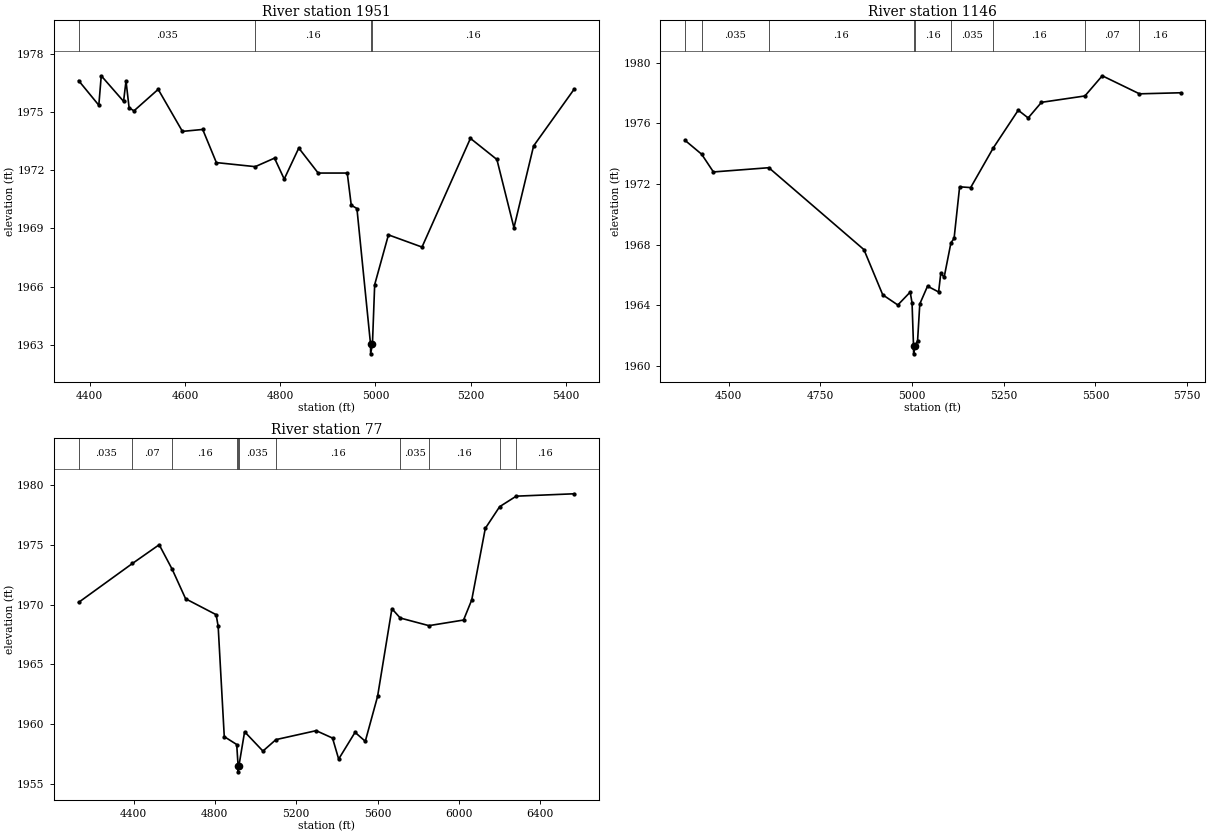
Type RM Length L Ch R = 1,1951,805,805,805
BEGIN DESCRIPTION:
377
END DESCRIPTION:
XS GIS Cut Line= 3
      1541978.46      6774542.08      1541861.05      6773929.84
      1542004.98      6773538.04
#Sta/Elev= 30
  4376.6 1976.63  4419.0 1975.36  4424.1 1976.88  4471.0 1975.56  4476.1 1976.61
  4482.6 1975.23  4492.8 1975.07  4543.7 1976.18  4594.6 1974.01  4637.2 1974.11
  4665.9 1972.40  4747.5 1972.19  4788.0 1972.63  4808.4 1971.55  4839.0 1973.15
  4879.7 1971.86  4940.8 1971.86  4949.2 1970.20  4961.1 1970.03  4989.7 1963.03
  4989.9 1962.53  4993.7 1963.03  4998.4 1966.10  5027.3 1968.67  5097.8 1968.04
  5199.5 1973.65  5255.1 1972.56  5290.9 1969.04  5332.2 1973.26  5417.4 1976.19
#Mann=4,-1,0
  4376.6   0.035       0  4747.5    0.16       0  4989.7    0.07       0
  4993.7    0.16       0
Bank Sta=4989.7,4993.7
Exp/Cntr=0.3,0.1

Type RM Length L Ch R = 1,1146,1069,1069,1069
BEGIN DESCRIPTION:
810
END DESCRIPTION:
XS GIS Cut Line= 3
      1542672.68      6774313.22      1542536.05      6773718.67
      1541916.07      6773312.73
#Sta/Elev= 30
  4381.2 1974.87  4426.3 1973.96  4458.4 1972.79  4609.5 1973.07  4868.8 1967.67
  4920.1 1964.69  4961.2 1964.02  4994.9 1964.87  5000.0 1964.16  5004.0 1961.30
  5004.3 1960.80  5008.0 1961.30  5015.1 1961.67  5021.1 1964.09  5042.2 1965.26
  5072.4 1964.88  5078.4 1966.12  5087.5 1965.85  5106.0 1968.12  5114.6 1968.41
  5129.7 1971.81  5159.8 1971.76  5221.4 1974.37  5289.5 1976.86  5316.6 1976.35
  5352.8 1977.38  5471.3 1977.80  5518.6 1979.13  5620.1 1977.94  5732.3 1978.01
#Mann=9,-1,0
  4381.2    0.16       0  4426.3   0.035       0  4609.5    0.16       0
  5004.0    0.07       0  5008.0    0.16       0  5106.0   0.035       0
  5221.4    0.16       0  5471.3    0.07       0  5620.1    0.16       0
Bank Sta=5004,5008
Exp/Cntr=0.3,0.1

Type RM Length L Ch R = 1,77,0,0,0
BEGIN DESCRIPTION:
376
END DESCRIPTION:
XS GIS Cut Line= 3
      1543370.57      6774254.09      1543360.92      6773394.20
      1541794.73      6773212.89
#Sta/Elev= 30
  4130.2 1970.19  4394.7 1973.45  4526.3 1975.02  4590.6 1972.95  4656.3 1970.49
  4806.3 1969.16  4816.3 1968.18  4846.3 1958.94  4907.5 1958.28  4914.3 1956.49
  4914.6 1955.99  4918.3 1956.49  4946.3 1959.35  5036.4 1957.73  5100.4 1958.69
  5298.1 1959.44  5378.6 1958.82  5408.8 1957.06  5489.4 1959.30  5539.7 1958.55
  5600.1 1962.31  5670.6 1969.66  5711.5 1968.88  5852.6 1968.24  6022.9 1968.71
  6063.2 1970.40  6129.8 1976.39  6200.4 1978.21  6281.8 1979.09  6566.8 1979.29
#Mann=11,-1,0
  4130.2   0.035       0  4394.7    0.07       0  4590.6    0.16       0
  4907.5   0.035       0  4914.3   0.035       0  4918.3   0.035       0
  5100.4    0.16       0  5711.5   0.035       0  5852.6    0.16       0
  6200.4    0.07       0  6281.8    0.16       0
Bank Sta=4914.3,4918.3
Exp/Cntr=0.3,0.1

Chan Stop Cuts=-1