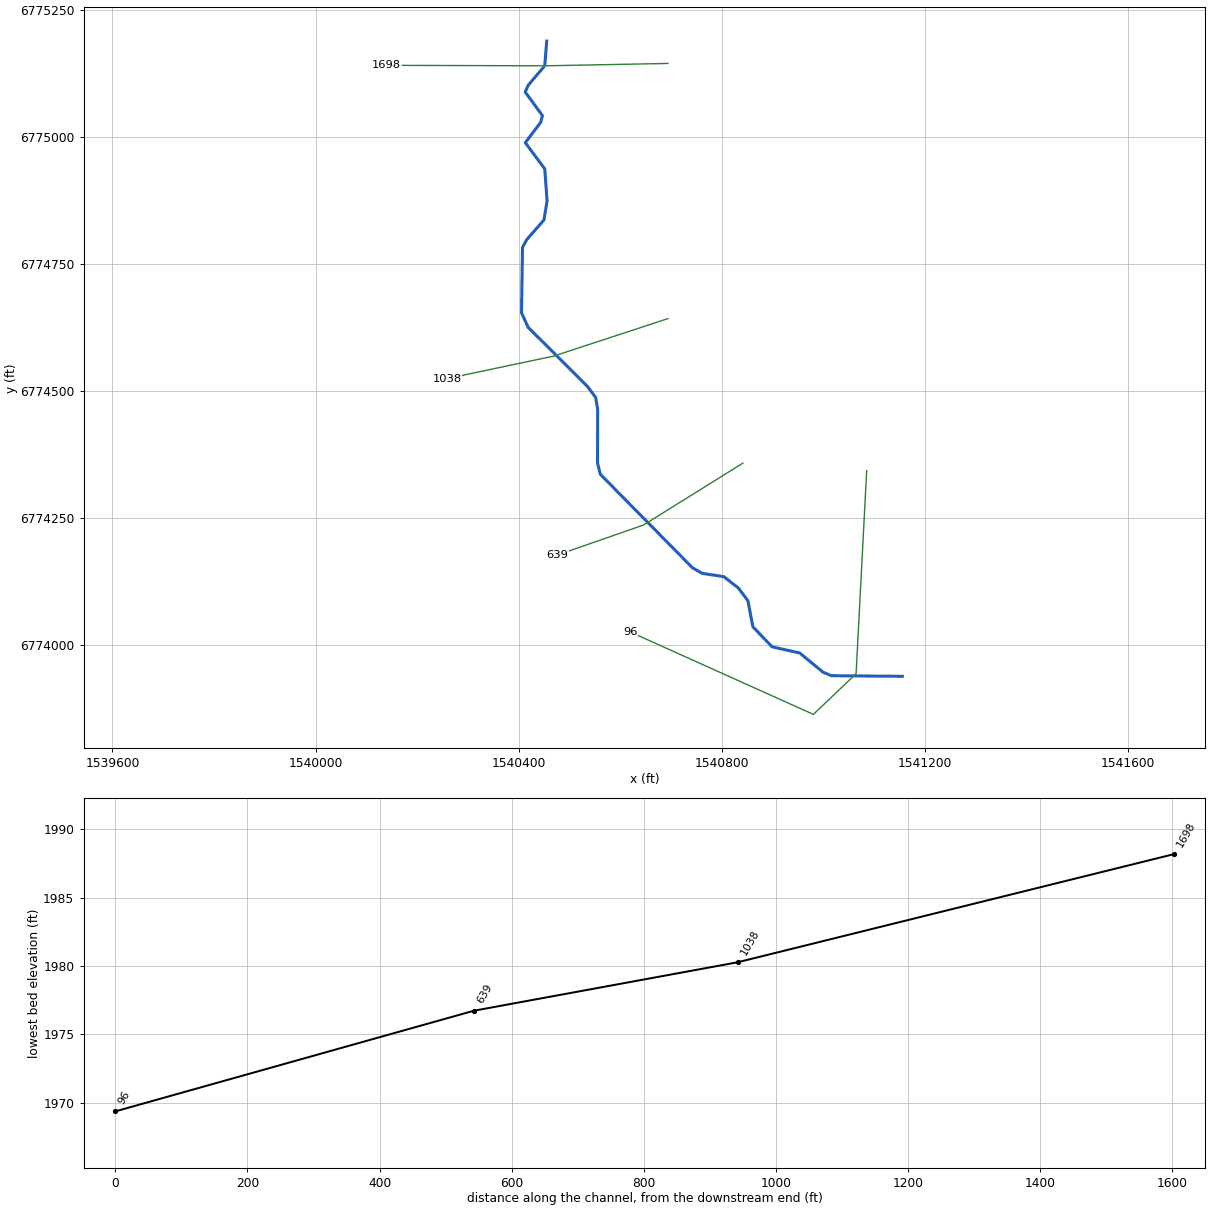
--- Elm 93.prj (project) ---

Proj Title=Elm 93 Base Level Engineering
Current Plan=p01
Default Exp/Contr=0.3,0.1
English Units
Geom File=g01
Flow File=f01
Plan File=p01
BEGIN DESCRIPTION:
Elm 93
END DESCRIPTION:

--- Elm 93.p01 (plan) ---

Plan Title=Multiple Run
Short Identifier=Multiple
Geom File=g01
Flow File=f01
Subcritical Flow
K Sum by GR= 0
Std Step Tol= 0.01
Critical Tol= 0.01
Num of Std Step Trials= 20
Max Error Tol= 0.3
Flow Tol Ratio= 0.001
Split Flow NTrial= 30
Split Flow Tol= 0.02
Split Flow Ratio= 0.02
Log Output Level= 0
Friction Slope Method= 1
Unsteady Friction Slope Method= 2
Unsteady Bridges Friction Slope Method= 1
Parabolic Critical Depth
Global Vel Dist=  1 , 1 , 1
Global Log Level= 0
CheckData=True
Encroach Param= -1, 0, 0, 0
BEGIN DESCRIPTION:
Multiple Run
END DESCRIPTION:

--- Elm 93.f01 (steady flow) ---

Flow Title=Multiple
Number of Profiles=7
Profile Names=10-year,25-year,50-year,1pct_min,100-year,1pct_plu,500-year
River Rch & RM= Elm 93,Reach-1,1698
     116     155     185     138     221     305     320
Boundary for River Rch & Prof#=Elm 93,Reach-1,1
Up Type=0
Dn Type=3
Dn Slope=0.005
Boundary for River Rch & Prof#=Elm 93,Reach-1,2
Up Type=0
Dn Type=3
Dn Slope=0.005
Boundary for River Rch & Prof#=Elm 93,Reach-1,3
Up Type=0
Dn Type=3
Dn Slope=0.005
Boundary for River Rch & Prof#=Elm 93,Reach-1,4
Up Type=0
Dn Type=3
Dn Slope=0.005
Boundary for River Rch & Prof#=Elm 93,Reach-1,5
Up Type=0
Dn Type=3
Dn Slope=0.005
Boundary for River Rch & Prof#=Elm 93,Reach-1,6
Up Type=0
Dn Type=3
Dn Slope=0.005
Boundary for River Rch & Prof#=Elm 93,Reach-1,7
Up Type=0
Dn Type=3
Dn Slope=0.005

--- Elm 93.g01 (geometry) ---

Geom Title=Existing Conditions

River Reach=Elm 93,Reach-1
Reach XY= 30
      1540455.00      6775188.00      1540451.02      6775139.36
      1540418.61      6775101.22      1540412.56      6775087.93
      1540446.48      6775041.33      1540443.04      6775028.01
      1540412.78      6774988.10      1540451.07      6774936.50
      1540455.69      6774872.94      1540449.31      6774835.69
      1540415.85      6774797.65      1540407.25      6774782.06
      1540405.37      6774653.16      1540418.37      6774624.68
      1540535.39      6774508.16      1540551.46      6774486.53
      1540555.27      6774463.11      1540554.98      6774357.99
      1540560.47      6774335.55      1540741.80      6774151.64
      1540761.09      6774140.55      1540803.57      6774134.11
      1540832.14      6774111.83      1540851.10      6774086.54
      1540860.76      6774035.49      1540898.66      6773996.02
      1540953.22      6773983.77      1540998.92      6773946.08
      1541015.47      6773939.15      1541155.00      6773938.00

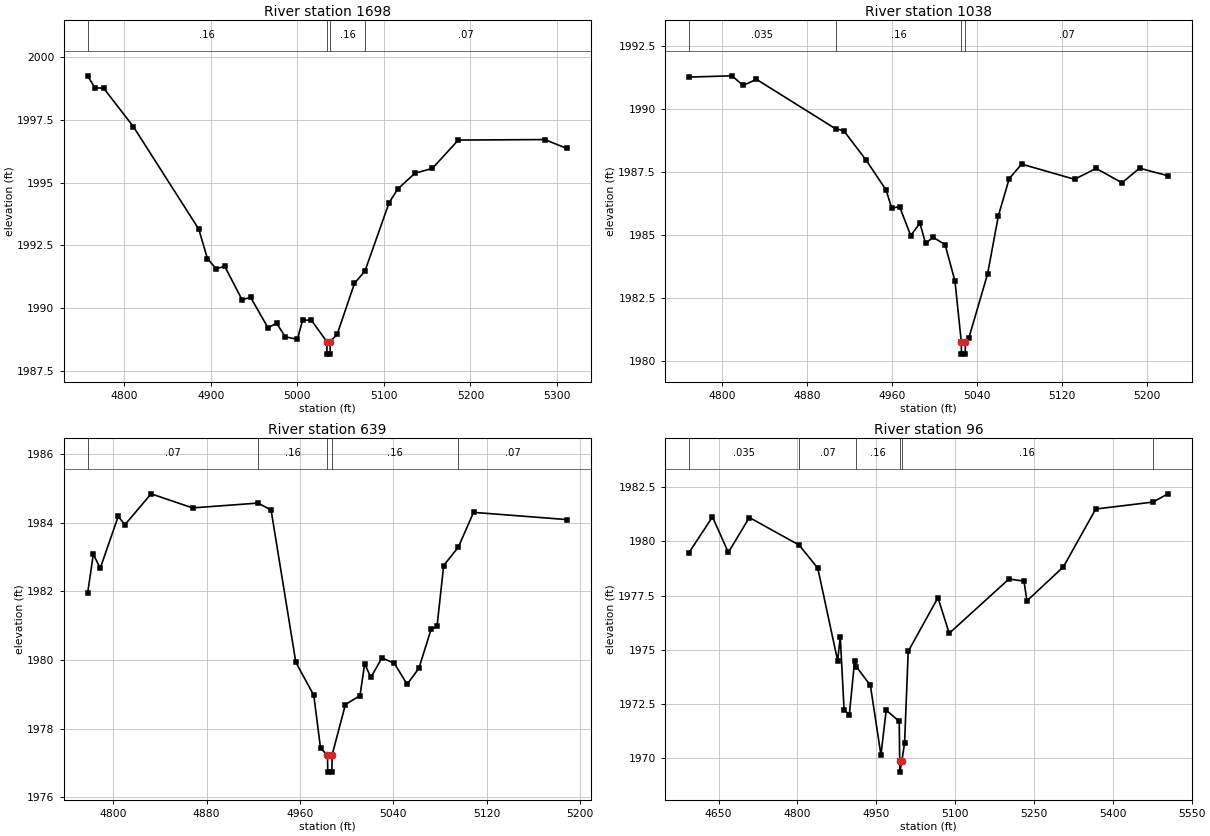
Type RM Length L Ch R = 1,1698,660,660,660
BEGIN DESCRIPTION:
460
END DESCRIPTION:
XS GIS Cut Line= 3
      1540693.47      6775144.00      1540451.02      6775139.36
      1540139.82      6775140.31
#Sta/Elev= 30
  4757.5 1999.26  4766.0 1998.78  4776.0 1998.77  4810.5 1997.23  4886.0 1993.15
  4896.0 1991.98  4906.0 1991.57  4916.0 1991.67  4936.0 1990.34  4946.0 1990.43
  4966.0 1989.22  4976.0 1989.40  4986.0 1988.86  5000.0 1988.76  5006.0 1989.52
  5016.0 1989.53  5034.0 1988.67  5034.3 1988.17  5037.8 1988.17  5038.0 1988.67
  5046.0 1988.96  5066.0 1990.99  5078.1 1991.48  5106.0 1994.20  5116.0 1994.75
  5136.0 1995.38  5156.0 1995.57  5186.0 1996.70  5286.0 1996.72  5311.2 1996.37
#Mann=4,-1,0
  4757.5    0.16       0  5034.0    0.07       0  5038.0    0.16       0
  5078.1    0.07       0
Bank Sta=5034,5038
Exp/Cntr=0.3,0.1

Type RM Length L Ch R = 1,1038,399,399,399
BEGIN DESCRIPTION:
813
END DESCRIPTION:
XS GIS Cut Line= 3
      1540693.45      6774641.81      1540468.21      6774567.96
      1540258.84      6774523.89
#Sta/Elev= 30
  4768.6 1991.25  4809.1 1991.30  4819.6 1990.92  4832.2 1991.16  4906.7 1989.20
  4914.3 1989.13  4935.4 1987.96  4954.3 1986.77  4959.5 1986.05  4966.9 1986.12
  4977.4 1984.97  4986.1 1985.46  4991.4 1984.66  4998.5 1984.90  5009.8 1984.61
  5019.1 1983.16  5025.0 1980.77  5025.2 1980.27  5028.7 1980.27  5029.0 1980.77
  5032.1 1980.90  5049.8 1983.45  5060.0 1985.76  5070.2 1987.23  5081.9 1987.80
  5131.7 1987.20  5152.0 1987.63  5176.4 1987.06  5192.9 1987.64  5219.6 1987.34
#Mann=4,-1,0
  4768.6   0.035       0  4906.7    0.16       0  5025.0    0.07       0
  5029.0    0.07       0
Bank Sta=5025,5029
Exp/Cntr=0.3,0.1

Type RM Length L Ch R = 1,639,543,543,543
BEGIN DESCRIPTION:
812
END DESCRIPTION:
XS GIS Cut Line= 3
      1540841.15      6774357.48      1540645.45      6774235.63
      1540475.57      6774176.54
#Sta/Elev= 30
  4778.0 1981.94  4782.9 1983.08  4788.8 1982.67  4804.2 1984.18  4810.0 1983.94
  4832.4 1984.84  4867.9 1984.43  4924.0 1984.57  4935.2 1984.37  4956.4 1979.93
  4971.8 1978.97  4977.6 1977.42  4983.5 1977.23  4983.8 1976.73  4987.3 1976.73
  4987.5 1977.23  4998.9 1978.70  5011.4 1978.96  5015.4 1979.89  5020.7 1979.49
  5030.2 1980.06  5040.8 1979.90  5051.8 1979.29  5061.9 1979.76  5072.3 1980.89
  5077.4 1980.98  5083.1 1982.75  5095.7 1983.29  5108.7 1984.30  5188.4 1984.09
#Mann=5,-1,0
  4778.0    0.07       0  4924.0    0.16       0  4983.5    0.07       0
  4987.5    0.16       0  5095.7    0.07       0
Bank Sta=4983.5,4987.5
Exp/Cntr=0.3,0.1

Type RM Length L Ch R = 1,96,0,0,0
BEGIN DESCRIPTION:
811
END DESCRIPTION:
XS GIS Cut Line= 4
      1541084.87      6774342.76      1541064.04      6773943.20
      1540980.00      6773863.00      1540619.76      6774025.08
#Sta/Elev= 30
  4593.5 1979.47  4638.3 1981.12  4668.4 1979.48  4708.4 1981.09  4803.2 1979.82
  4838.6 1978.76  4876.4 1974.50  4881.4 1975.60  4888.7 1972.23  4898.7 1972.02
  4908.7 1974.49  4911.8 1974.23  4938.7 1973.36  4958.8 1970.16  4968.8 1972.22
  4993.6 1971.71  4994.5 1969.87  4994.8 1969.37  4998.5 1969.87  5003.8 1970.72
  5010.7 1974.93  5067.3 1977.40  5088.7 1975.76  5202.4 1978.26  5231.0 1978.16
  5236.5 1977.25  5306.0 1978.82  5367.5 1981.48  5476.2 1981.80  5504.8 1982.18
#Mann=6,-1,0
  4593.5   0.035       0  4803.2    0.07       0  4911.8    0.16       0
  4994.5    0.07       0  4998.5    0.16       0  5476.2    0.07       0
Bank Sta=4994.5,4998.5
Exp/Cntr=0.3,0.1

Chan Stop Cuts=-1