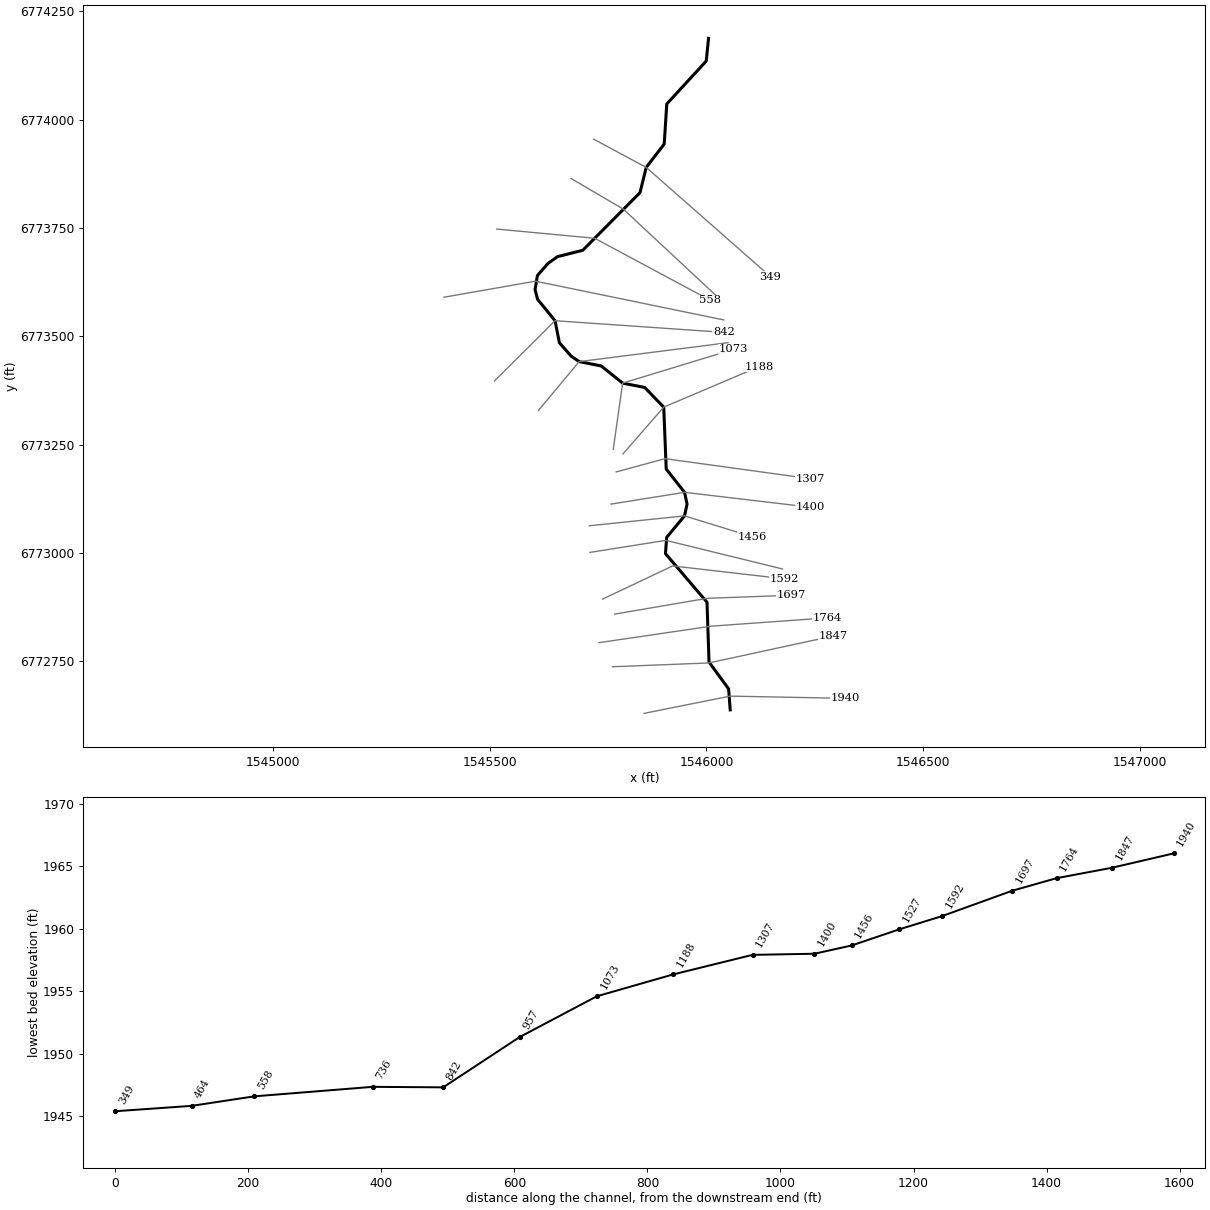
--- Elm 94.prj (project) ---

Proj Title=Elm 94 Base Level Engineering
Current Plan=p01
Default Exp/Contr=0.3,0.1
English Units
Geom File=g01
Flow File=f01
Plan File=p01
BEGIN DESCRIPTION:
Elm 94
END DESCRIPTION:

--- Elm 94.p01 (plan) ---

Plan Title=Multiple Run
Short Identifier=Multiple
Geom File=g01
Flow File=f01
Subcritical Flow
K Sum by GR= 0
Std Step Tol= 0.01
Critical Tol= 0.01
Num of Std Step Trials= 20
Max Error Tol= 0.3
Flow Tol Ratio= 0.001
Split Flow NTrial= 30
Split Flow Tol= 0.02
Split Flow Ratio= 0.02
Log Output Level= 0
Friction Slope Method= 1
Unsteady Friction Slope Method= 2
Unsteady Bridges Friction Slope Method= 1
Parabolic Critical Depth
Global Vel Dist=  1 , 1 , 1
Global Log Level= 0
CheckData=True
Encroach Param= -1, 0, 0, 0
BEGIN DESCRIPTION:
Multiple Run
END DESCRIPTION:

--- Elm 94.f01 (steady flow) ---

Flow Title=Multiple
Number of Profiles=7
Profile Names=10-year,25-year,50-year,1pct_min,100-year,1pct_plu,500-year
River Rch & RM= Elm 94,Reach-1,1940
      48      59      68      49      78     108     104
Boundary for River Rch & Prof#=Elm 94,Reach-1,1
Up Type=0
Dn Type=3
Dn Slope=0.005
Boundary for River Rch & Prof#=Elm 94,Reach-1,2
Up Type=0
Dn Type=3
Dn Slope=0.005
Boundary for River Rch & Prof#=Elm 94,Reach-1,3
Up Type=0
Dn Type=3
Dn Slope=0.005
Boundary for River Rch & Prof#=Elm 94,Reach-1,4
Up Type=0
Dn Type=3
Dn Slope=0.005
Boundary for River Rch & Prof#=Elm 94,Reach-1,5
Up Type=0
Dn Type=3
Dn Slope=0.005
Boundary for River Rch & Prof#=Elm 94,Reach-1,6
Up Type=0
Dn Type=3
Dn Slope=0.005
Boundary for River Rch & Prof#=Elm 94,Reach-1,7
Up Type=0
Dn Type=3
Dn Slope=0.005

--- Elm 94.g01 (geometry) ---

Geom Title=Existing Conditions

River Reach=Elm 94,Reach-1
Reach XY= 30
      1546055.00      6772638.00      1546051.35      6772686.49
      1546006.13      6772748.47      1546001.44      6772886.53
      1545905.61      6772998.63      1545908.37      6773036.26
      1545949.58      6773085.80      1545955.39      6773113.00
      1545949.62      6773140.18      1545907.30      6773193.93
      1545901.55      6773336.75      1545857.58      6773382.29
      1545806.77      6773392.20      1545757.16      6773431.89
      1545706.42      6773441.86      1545687.94      6773454.49
      1545660.72      6773485.45      1545650.73      6773536.24
      1545610.30      6773585.84      1545604.60      6773608.27
      1545609.98      6773640.55      1545634.32      6773668.37
      1545656.37      6773684.11      1545714.66      6773698.79
      1545846.86      6773831.94      1545861.14      6773890.17
      1545902.67      6773943.97      1545908.61      6774036.50
      1545999.67      6774135.49      1546005.00      6774188.00

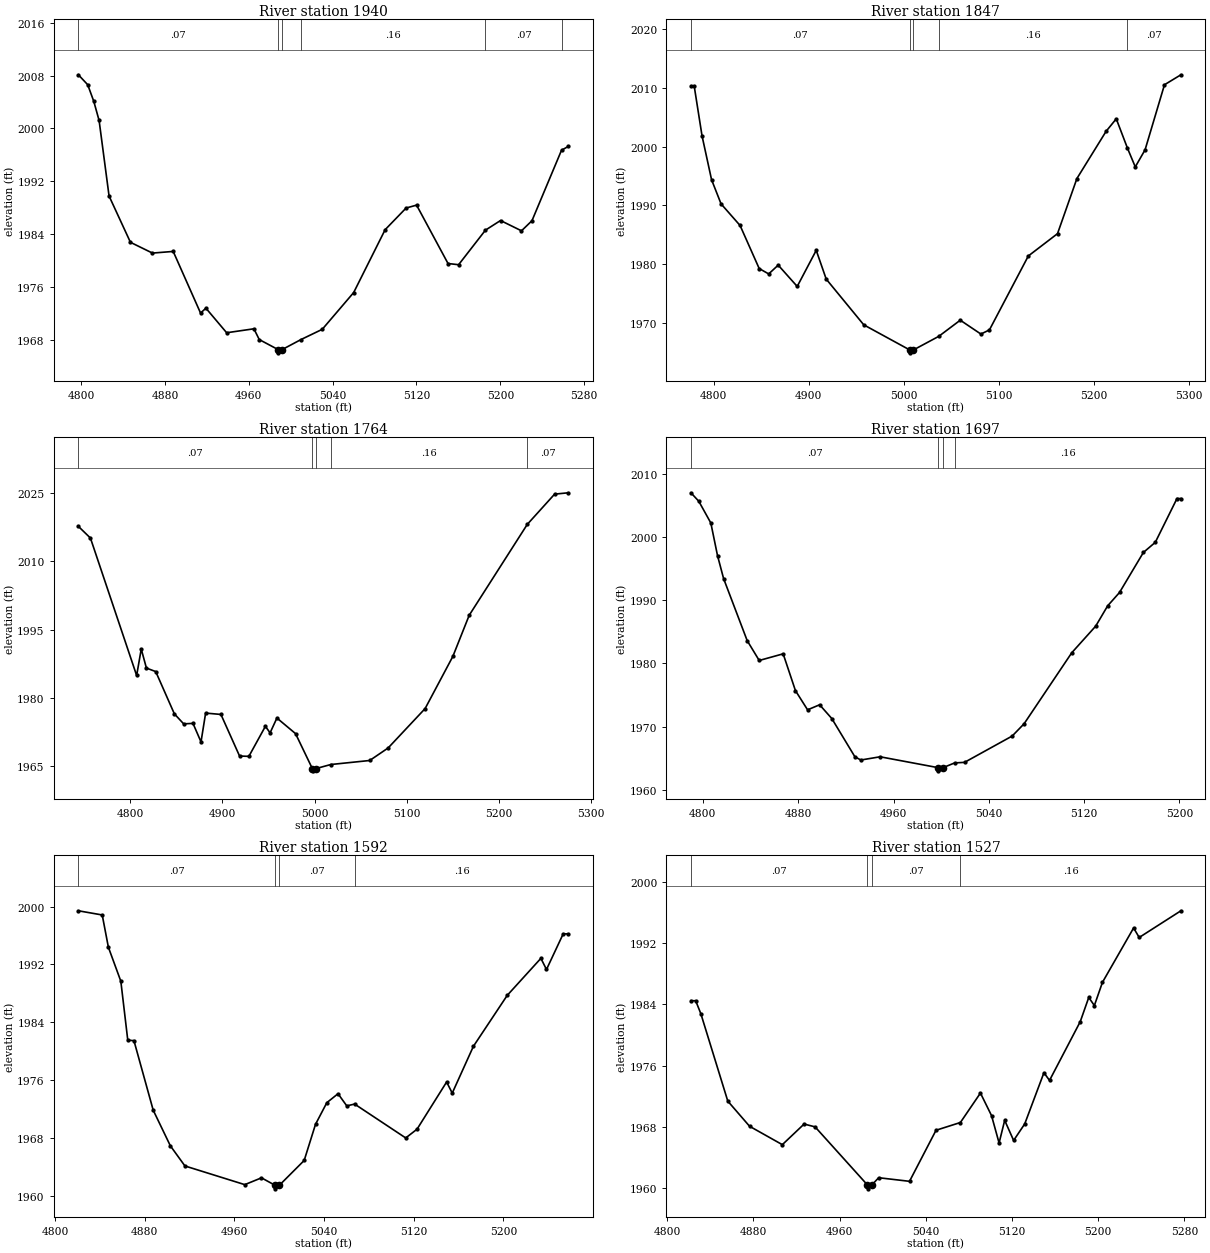
Type RM Length L Ch R = 1,1940,93,93,93
BEGIN DESCRIPTION:
Elm 94 1939.882
END DESCRIPTION:
XS GIS Cut Line= 3
      1545856.23      6772629.98      1546054.88      6772669.80
      1546319.73      6772664.70
#Sta/Elev= 30
  4797.4 2008.11  4806.3 2006.61  4812.1 2004.10  4817.2 2001.19  4826.7 1989.76
  4847.1 1982.75  4868.1 1981.12  4887.9 1981.37  4914.0 1972.04  4919.1 1972.78
  4938.9 1969.06  4964.9 1969.66  4970.0 1968.03  4987.9 1966.52  4988.2 1966.02
  4991.9 1966.52  5009.8 1968.03  5030.1 1969.58  5060.1 1975.15  5090.1 1984.66
  5110.1 1987.94  5120.1 1988.38  5150.1 1979.54  5160.2 1979.36  5185.8 1984.59
  5200.2 1986.05  5220.2 1984.49  5230.2 1986.02  5258.4 1996.69  5264.9 1997.27
#Mann=6,-1,0
  4797.4    0.07       0  4987.9    0.07       0  4991.9    0.07       0
  5009.8    0.16       0  5185.8    0.07       0  5258.4    0.16       0
Bank Sta=4987.9,4991.9
Exp/Cntr=0.3,0.1

Type RM Length L Ch R = 1,1847,83,83,83
BEGIN DESCRIPTION:
Elm 94 1847.43
END DESCRIPTION:
XS GIS Cut Line= 3
      1545783.29      6772737.62      1546005.52      6772746.30
      1546291.87      6772808.40
#Sta/Elev= 30
  4776.2 2010.35  4779.6 2010.35  4787.9 2001.81  4797.9 1994.36  4807.9 1990.24
  4827.9 1986.56  4848.0 1979.23  4858.0 1978.31  4868.0 1979.81  4888.0 1976.18
  4908.0 1982.33  4918.5 1977.43  4958.0 1969.64  5006.3 1965.37  5006.5 1964.87
  5010.3 1965.37  5036.9 1967.68  5059.5 1970.43  5081.2 1968.07  5090.2 1968.78
  5131.1 1981.37  5161.8 1985.17  5182.2 1994.56  5212.9 2002.60  5223.6 2004.73
  5235.4 1999.72  5243.6 1996.54  5253.9 1999.45  5274.3 2010.53  5291.6 2012.23
#Mann=5,-1,0
  4776.2    0.07       0  5006.3    0.07       0  5010.3    0.07       0
  5036.9    0.16       0  5235.4    0.07       0
Bank Sta=5006.3,5010.3
Exp/Cntr=0.3,0.1

Type RM Length L Ch R = 1,1764,67,67,67
BEGIN DESCRIPTION:
Elm 94 1763.53
END DESCRIPTION:
XS GIS Cut Line= 3
      1545752.03      6772793.17      1546012.46      6772831.37
      1546279.86      6772850.47
#Sta/Elev= 30
  4743.8 2017.71  4756.9 2015.14  4807.0 1984.97  4812.0 1990.77  4817.6 1986.60
  4827.7 1985.83  4847.9 1976.55  4858.0 1974.35  4868.1 1974.46  4876.8 1970.39
  4881.8 1976.72  4898.4 1976.42  4918.6 1967.29  4928.7 1967.22  4946.6 1973.81
  4951.7 1972.38  4959.1 1975.63  4979.3 1972.21  4997.5 1964.54  4997.7 1964.04
  5001.5 1964.54  5017.6 1965.43  5059.7 1966.31  5079.7 1969.06  5119.8 1977.71
  5149.9 1989.17  5167.6 1998.19  5230.6 2018.15  5260.2 2024.78  5275.1 2025.08
#Mann=5,-1,0
  4743.8    0.07       0  4997.5    0.07       0  5001.5    0.07       0
  5017.6    0.16       0  5230.6    0.07       0
Bank Sta=4997.5,5001.5
Exp/Cntr=0.3,0.1

Type RM Length L Ch R = 1,1697,105,105,105
BEGIN DESCRIPTION:
Elm 94 1697.11
END DESCRIPTION:
XS GIS Cut Line= 3
      1545788.51      6772859.15      1546002.04      6772895.60
      1546196.50      6772902.55
#Sta/Elev= 30
  4790.0 2006.97  4796.6 2005.63  4806.7 2002.20  4812.3 1997.05  4817.4 1993.42
  4837.2 1983.61  4847.3 1980.47  4867.4 1981.52  4877.7 1975.71  4887.9 1972.67
  4898.0 1973.47  4908.2 1971.30  4927.6 1965.25  4932.6 1964.74  4948.8 1965.25
  4997.5 1963.53  4997.7 1963.03  5001.5 1963.53  5011.3 1964.28  5019.6 1964.37
  5059.6 1968.53  5069.6 1970.47  5109.6 1981.69  5129.7 1985.90  5139.7 1989.10
  5149.7 1991.22  5169.7 1997.54  5179.7 1999.14  5197.9 2006.06  5201.2 2006.06
#Mann=4,-1,0
  4790.0    0.07       0  4997.5    0.07       0  5001.5    0.07       0
  5011.3    0.16       0
Bank Sta=4997.5,5001.5
Exp/Cntr=0.3,0.1

Type RM Length L Ch R = 1,1592,65,65,65
BEGIN DESCRIPTION:
Elm 94 1591.99
END DESCRIPTION:
XS GIS Cut Line= 3
      1545760.76      6772893.89      1545922.18      6772970.26
      1546179.12      6772940.74
#Sta/Elev= 30
  4820.8 1999.42  4842.1 1998.84  4847.6 1994.38  4858.7 1989.69  4864.9 1981.54
  4870.4 1981.48  4887.6 1971.87  4902.9 1966.95  4915.9 1964.17  4969.3 1961.59
  4984.2 1962.53  4996.2 1961.51  4996.4 1961.01  5000.2 1961.51  5022.3 1964.93
  5032.4 1969.92  5042.5 1972.91  5052.5 1974.15  5060.3 1972.47  5067.3 1972.72
  5112.9 1968.04  5123.0 1969.25  5149.4 1975.77  5154.4 1974.23  5173.3 1980.70
  5203.5 1987.74  5233.5 1992.85  5238.5 1991.31  5253.4 1996.23  5258.0 1996.23
#Mann=4,-1,0
  4820.8    0.07       0  4996.2    0.07       0  5000.2    0.07       0
  5067.3    0.16       0
Bank Sta=4996.2,5000.2
Exp/Cntr=0.3,0.1

Type RM Length L Ch R = 1,1527,71,71,71
BEGIN DESCRIPTION:
Elm 94 1527.39
END DESCRIPTION:
XS GIS Cut Line= 3
      1545731.25      6773001.51      1545906.56      6773029.28
      1546175.69      6772963.30
#Sta/Elev= 30
  4822.1 1984.47  4826.5 1984.47  4831.3 1982.78  4856.3 1971.38  4876.5 1968.10
  4906.9 1965.70  4927.1 1968.39  4937.3 1968.02  4985.9 1960.44  4986.1 1959.94
  4989.9 1960.44  4996.3 1961.39  5024.9 1960.92  5049.5 1967.58  5072.1 1968.59
  5090.7 1972.43  5101.0 1969.49  5108.0 1965.92  5113.2 1968.87  5121.5 1966.25
  5131.8 1968.41  5149.6 1975.08  5154.8 1974.08  5183.3 1981.74  5191.2 1984.90
  5196.4 1983.84  5203.9 1986.87  5232.8 1993.96  5238.0 1992.72  5276.7 1996.20
#Mann=4,-1,0
  4822.1    0.07       0  4985.9    0.07       0  4989.9    0.07       0
  5072.1    0.16       0
Bank Sta=4985.9,4989.9
Exp/Cntr=0.3,0.1

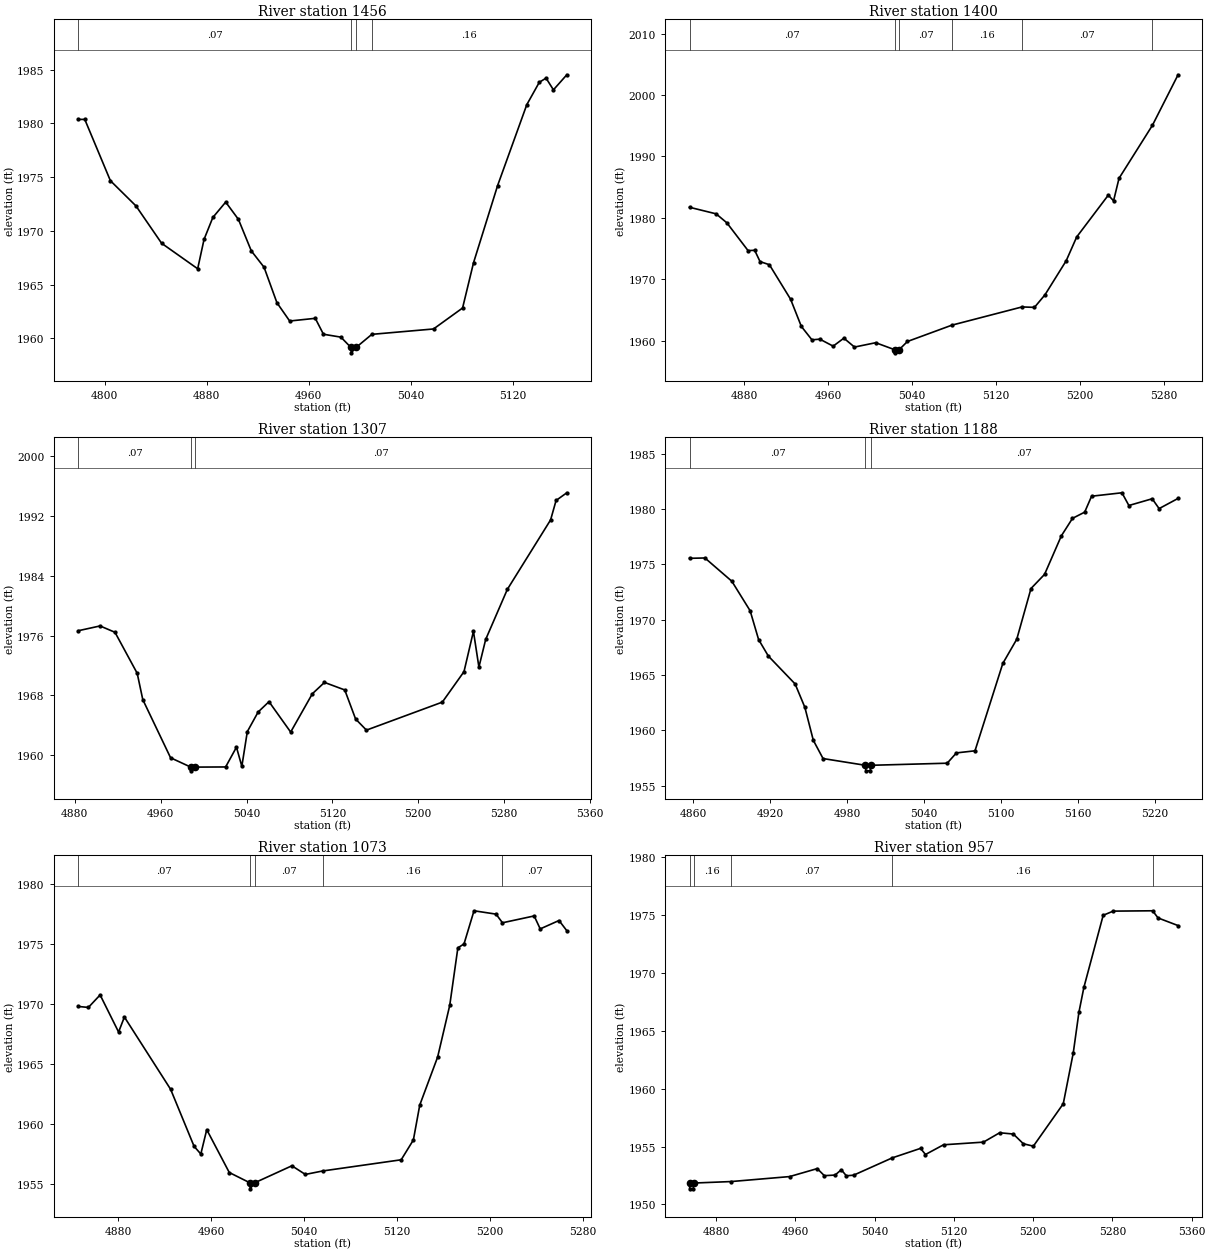
Type RM Length L Ch R = 1,1456,56,56,56
BEGIN DESCRIPTION:
Elm 94 1455.734
END DESCRIPTION:
XS GIS Cut Line= 3
      1545729.97      6773063.00      1545949.58      6773085.80
      1546105.00      6773038.00
#Sta/Elev= 30
  4779.2 1980.37  4784.3 1980.37  4804.4 1974.67  4824.5 1972.32  4844.6 1968.85
  4872.9 1966.48  4877.9 1969.21  4884.8 1971.25  4894.9 1972.68  4904.9 1971.07
  4915.0 1968.14  4925.0 1966.62  4935.1 1963.32  4945.1 1961.62  4965.2 1961.87
  4971.6 1960.39  4985.3 1960.12  4993.2 1959.16  4993.4 1958.66  4997.2 1959.16
  5009.6 1960.38  5058.0 1960.88  5080.8 1962.83  5089.4 1967.04  5108.3 1974.22
  5131.2 1981.74  5141.0 1983.82  5146.3 1984.21  5152.1 1983.12  5162.6 1984.52
#Mann=4,-1,0
  4779.2    0.07       0  4993.2    0.07       0  4997.2    0.07       0
  5009.6    0.16       0
Bank Sta=4993.2,4997.2
Exp/Cntr=0.3,0.1

Type RM Length L Ch R = 1,1400,93,93,93
BEGIN DESCRIPTION:
Elm 94 3889
END DESCRIPTION:
XS GIS Cut Line= 3
      1545779.99      6773113.00      1545949.62      6773140.18
      1546240.80      6773105.77
#Sta/Elev= 30
  4828.2 1981.72  4853.5 1980.65  4863.7 1979.19  4883.9 1974.66  4890.2 1974.71
  4895.3 1972.87  4904.2 1972.36  4924.4 1966.73  4934.6 1962.31  4944.7 1960.12
  4952.2 1960.23  4964.9 1959.09  4975.1 1960.39  4985.2 1958.94  5005.4 1959.65
  5023.6 1958.50  5023.8 1958.00  5027.6 1958.50  5035.6 1959.85  5077.9 1962.51
  5144.7 1965.48  5156.5 1965.41  5166.5 1967.45  5186.7 1973.00  5196.7 1976.88
  5226.8 1983.70  5231.8 1982.77  5237.0 1986.44  5268.8 1995.08  5293.2 2003.31
#Mann=6,-1,0
  4828.2    0.07       0  5023.6    0.07       0  5027.6    0.07       0
  5077.9    0.16       0  5144.7    0.07       0  5268.8    0.16       0
Bank Sta=5023.6,5027.6
Exp/Cntr=0.3,0.1

Type RM Length L Ch R = 1,1307,119,119,119
BEGIN DESCRIPTION:
Elm 94 3888
END DESCRIPTION:
XS GIS Cut Line= 3
      1545791.96      6773187.27      1545904.68      6773217.86
      1546239.91      6773171.64
#Sta/Elev= 30
  4883.2 1976.67  4903.5 1977.31  4917.4 1976.46  4938.1 1970.97  4943.3 1967.45
  4969.2 1959.66  4988.0 1958.41  4988.2 1957.91  4992.0 1958.41  5020.5 1958.43
  5030.6 1961.08  5035.6 1958.51  5040.7 1963.16  5050.8 1965.79  5060.9 1967.17
  5081.1 1963.10  5101.3 1968.23  5112.6 1969.75  5131.5 1968.74  5141.6 1964.85
  5151.7 1963.36  5222.4 1967.11  5242.6 1971.19  5251.4 1976.59  5256.5 1971.80
  5262.8 1975.50  5283.0 1982.21  5323.3 1991.51  5328.4 1994.11  5338.4 1995.14
#Mann=3,-1,0
  4883.2    0.07       0  4988.0    0.07       0  4992.0    0.07       0
Bank Sta=4988,4992
Exp/Cntr=0.3,0.1

Type RM Length L Ch R = 1,1188,115,115,115
BEGIN DESCRIPTION:
Elm 94 3887
END DESCRIPTION:
XS GIS Cut Line= 3
      1545807.60      6773228.94      1545901.55      6773336.75
      1546120.88      6773429.92
#Sta/Elev= 30
  4857.0 1975.55  4869.0 1975.58  4890.0 1973.48  4904.3 1970.81  4910.9 1968.21
  4918.5 1966.72  4939.4 1964.20  4947.0 1962.09  4953.6 1959.11  4961.2 1957.46
  4994.3 1956.85  4994.6 1956.35  4998.1 1956.35  4998.3 1956.85  5058.1 1957.04
  5065.3 1957.97  5079.8 1958.16  5101.5 1966.05  5112.4 1968.24  5123.5 1972.82
  5134.1 1974.10  5147.2 1977.58  5155.9 1979.16  5165.4 1979.72  5170.8 1981.16
  5194.5 1981.47  5199.9 1980.32  5218.1 1980.93  5223.5 1980.04  5238.3 1980.96
#Mann=3,-1,0
  4857.0    0.07       0  4994.3    0.07       0  4998.3    0.07       0
Bank Sta=4994.3,4998.3
Exp/Cntr=0.3,0.1

Type RM Length L Ch R = 1,1073,116,116,116
BEGIN DESCRIPTION:
Elm 94 3886
END DESCRIPTION:
XS GIS Cut Line= 3
      1545785.03      6773239.34      1545806.77      6773392.20
      1546061.40      6773469.83
#Sta/Elev= 30
  4845.6 1969.79  4854.3 1969.71  4864.4 1970.75  4880.3 1967.66  4885.3 1968.91
  4925.1 1962.89  4945.3 1958.14  4951.1 1957.50  4956.2 1959.53  4975.6 1955.96
  4993.4 1955.10  4993.6 1954.60  4997.4 1955.10  5029.5 1956.52  5041.1 1955.80
  5056.1 1956.09  5123.6 1957.02  5134.1 1958.67  5139.6 1961.58  5155.0 1965.58
  5165.4 1969.88  5172.4 1974.67  5177.7 1975.00  5186.3 1977.76  5205.3 1977.48
  5210.8 1976.76  5238.1 1977.33  5243.3 1976.25  5259.5 1976.95  5266.2 1976.10
#Mann=5,-1,0
  4845.6    0.07       0  4993.4    0.07       0  4997.4    0.07       0
  5056.1    0.16       0  5210.8    0.07       0
Bank Sta=4993.4,4997.4
Exp/Cntr=0.3,0.1

Type RM Length L Ch R = 1,957,115,115,115
BEGIN DESCRIPTION:
Elm 94 3884
END DESCRIPTION:
XS GIS Cut Line= 3
      1545612.32      6773329.05      1545706.42      6773441.86
      1546049.95      6773485.56
#Sta/Elev= 30
  4853.1 1951.84  4853.3 1951.34  4856.8 1951.34  4857.1 1951.84  4895.1 1951.97
  4954.1 1952.40  4982.0 1953.09  4989.2 1952.48  5000.0 1952.53  5006.3 1952.99
  5011.4 1952.47  5018.7 1952.52  5057.8 1954.02  5086.3 1954.84  5091.3 1954.31
  5109.5 1955.15  5149.8 1955.38  5166.2 1956.19  5180.0 1956.08  5190.1 1955.24
  5200.2 1955.03  5230.4 1958.70  5240.5 1963.10  5246.2 1966.61  5251.2 1968.76
  5270.7 1975.00  5280.8 1975.36  5320.6 1975.39  5326.1 1974.77  5346.3 1974.11
#Mann=5,-1,0
  4853.1    0.07       0  4857.1    0.16       0  4895.1    0.07       0
  5057.8    0.16       0  5320.6    0.07       0
Bank Sta=4853.1,4857.1
Exp/Cntr=0.3,0.1

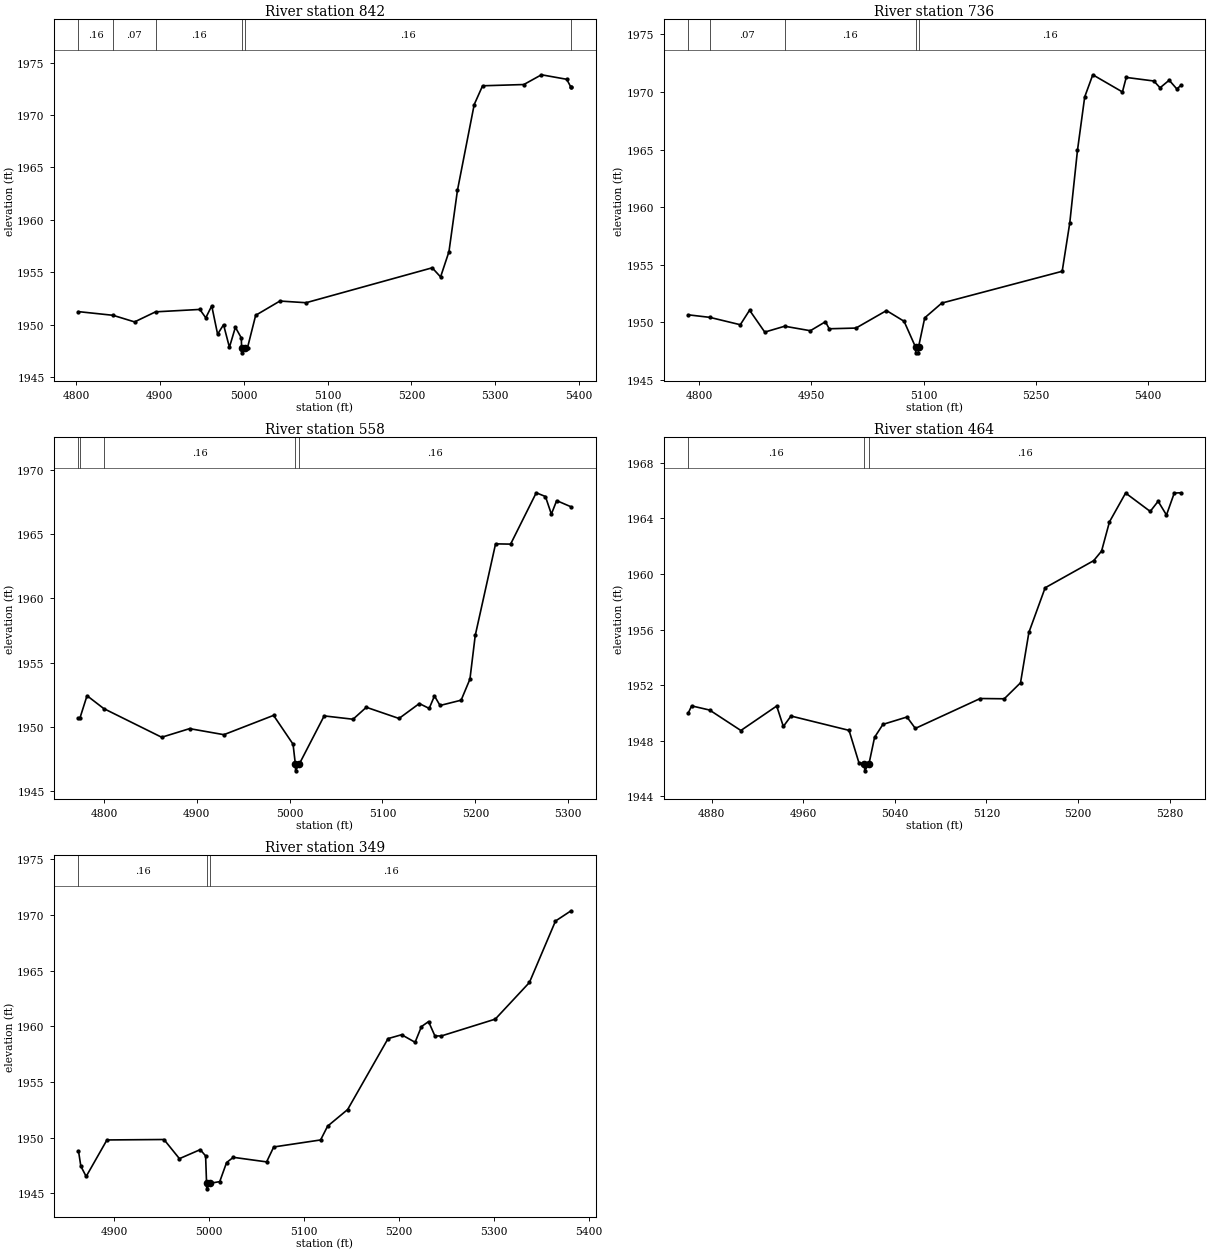
Type RM Length L Ch R = 1,842,106,106,106
BEGIN DESCRIPTION:
Elm 94 3880
END DESCRIPTION:
XS GIS Cut Line= 3
      1545511.05      6773397.32      1545650.73      6773536.24
      1546040.21      6773509.41
#Sta/Elev= 30
  4803.0 1951.25  4844.2 1950.90  4869.9 1950.27  4894.9 1951.23  4947.7 1951.46
  4954.8 1950.66  4961.9 1951.80  4968.9 1949.10  4976.0 1950.00  4983.0 1947.85
  4990.1 1949.76  4997.2 1948.74  4997.5 1947.82  4997.7 1947.32  5001.5 1947.82
  5004.6 1947.82  5014.3 1950.90  5043.2 1952.26  5074.4 1952.10  5224.8 1955.43
  5234.8 1954.56  5244.8 1956.97  5254.9 1962.81  5274.9 1971.00  5284.9 1972.79
  5334.1 1972.91  5355.1 1973.84  5385.2 1973.41  5389.9 1972.71  5390.4 1972.63
#Mann=6,-1,0
  4803.0    0.16       0  4844.2    0.07       0  4894.9    0.16       0
  4997.5    0.07       0  5001.5    0.16       0  5389.9    0.07       0
Bank Sta=4997.5,5001.5
Exp/Cntr=0.3,0.1

Type RM Length L Ch R = 1,736,178,178,178
BEGIN DESCRIPTION:
Elm 94 3879
END DESCRIPTION:
XS GIS Cut Line= 3
      1545394.26      6773590.47      1545605.53      6773627.53
      1546040.21      6773538.05
#Sta/Elev= 30
  4785.5 1950.66  4814.4 1950.44  4855.1 1949.80  4867.5 1951.06  4887.8 1949.16
  4914.4 1949.67  4948.7 1949.28  4968.9 1950.06  4973.9 1949.45  5009.7 1949.51
  5050.5 1951.03  5074.0 1950.10  5089.3 1947.86  5089.6 1947.36  5093.1 1947.36
  5093.3 1947.86  5101.6 1950.40  5124.4 1951.68  5285.3 1954.44  5295.5 1958.67
  5305.7 1964.93  5315.4 1969.58  5326.2 1971.50  5365.8 1970.01  5370.9 1971.27
  5407.8 1970.96  5416.1 1970.37  5428.3 1971.03  5438.5 1970.27  5443.8 1970.57
#Mann=5,-1,0
  4785.5    0.16       0  4814.4    0.07       0  4914.4    0.16       0
  5089.3    0.07       0  5093.3    0.16       0
Bank Sta=5089.3,5093.3
Exp/Cntr=0.3,0.1

Type RM Length L Ch R = 1,558,94,94,94
BEGIN DESCRIPTION:
Elm 94 3881
END DESCRIPTION:
XS GIS Cut Line= 3
      1545515.79      6773747.83      1545742.19      6773726.52
      1546009.34      6773583.33
#Sta/Elev= 30
  4772.6 1950.71  4774.2 1950.71  4781.8 1952.44  4799.8 1951.44  4862.2 1949.21
  4892.3 1949.88  4929.2 1949.41  4982.7 1950.91  5003.7 1948.67  5006.2 1947.10
  5006.4 1946.60  5010.2 1947.10  5037.2 1950.87  5068.3 1950.61  5082.6 1951.54
  5117.8 1950.67  5139.7 1951.83  5150.3 1951.45  5156.0 1952.42  5162.0 1951.68
  5184.7 1952.09  5194.2 1953.73  5199.9 1957.12  5221.8 1964.24  5238.0 1964.22
  5265.6 1968.21  5275.5 1967.92  5281.9 1966.55  5287.6 1967.60  5303.1 1967.12
#Mann=5,-1,0
  4772.6    0.16       0  4774.2    0.07       0  4799.8    0.16       0
  5006.2    0.07       0  5010.2    0.16       0
Bank Sta=5006.2,5010.2
Exp/Cntr=0.3,0.1

Type RM Length L Ch R = 1,464,115,115,115
BEGIN DESCRIPTION:
Elm 94 3882
END DESCRIPTION:
XS GIS Cut Line= 3
      1545687.54      6773864.64      1545808.69      6773793.50
      1546020.64      6773595.85
#Sta/Elev= 30
  4859.5 1949.99  4862.5 1950.51  4878.2 1950.21  4905.5 1948.74  4936.8 1950.50
  4942.6 1949.03  4949.3 1949.78  5000.0 1948.75  5008.6 1946.43  5013.4 1946.34
  5013.7 1945.84  5017.4 1946.34  5022.3 1948.25  5029.6 1949.18  5050.6 1949.71
  5057.9 1948.89  5114.6 1951.04  5135.6 1951.02  5149.8 1952.17  5157.1 1955.79
  5171.3 1959.00  5213.7 1960.95  5220.6 1961.64  5227.5 1963.74  5241.6 1965.81
  5263.1 1964.49  5270.0 1965.22  5277.3 1964.23  5284.1 1965.81  5289.8 1965.83
#Mann=3,-1,0
  4859.5    0.16       0  5013.4    0.07       0  5017.4    0.16       0
Bank Sta=5013.4,5017.4
Exp/Cntr=0.3,0.1

Type RM Length L Ch R = 1,349,0,0,0
BEGIN DESCRIPTION:
Elm 94 3883
END DESCRIPTION:
XS GIS Cut Line= 3
      1545739.92      6773955.28      1545861.14      6773890.17
      1546147.67      6773638.15
#Sta/Elev= 30
  4862.4 1948.82  4864.9 1947.44  4870.5 1946.52  4892.4 1949.80  4952.5 1949.84
  4968.8 1948.12  4990.7 1948.93  4996.4 1948.37  4997.4 1945.91  4997.6 1945.41
  5001.4 1945.91  5011.3 1946.06  5018.5 1947.77  5025.6 1948.24  5060.7 1947.83
  5068.2 1949.17  5117.6 1949.80  5125.0 1951.04  5146.1 1952.53  5188.7 1958.90
  5203.0 1959.25  5217.2 1958.57  5223.9 1959.98  5231.4 1960.43  5238.1 1959.14
  5244.9 1959.14  5301.7 1960.65  5337.7 1963.94  5365.2 1969.46  5381.6 1970.38
#Mann=3,-1,0
  4862.4    0.16       0  4997.4    0.07       0  5001.4    0.16       0
Bank Sta=4997.4,5001.4
Exp/Cntr=0.3,0.1

Chan Stop Cuts=-1