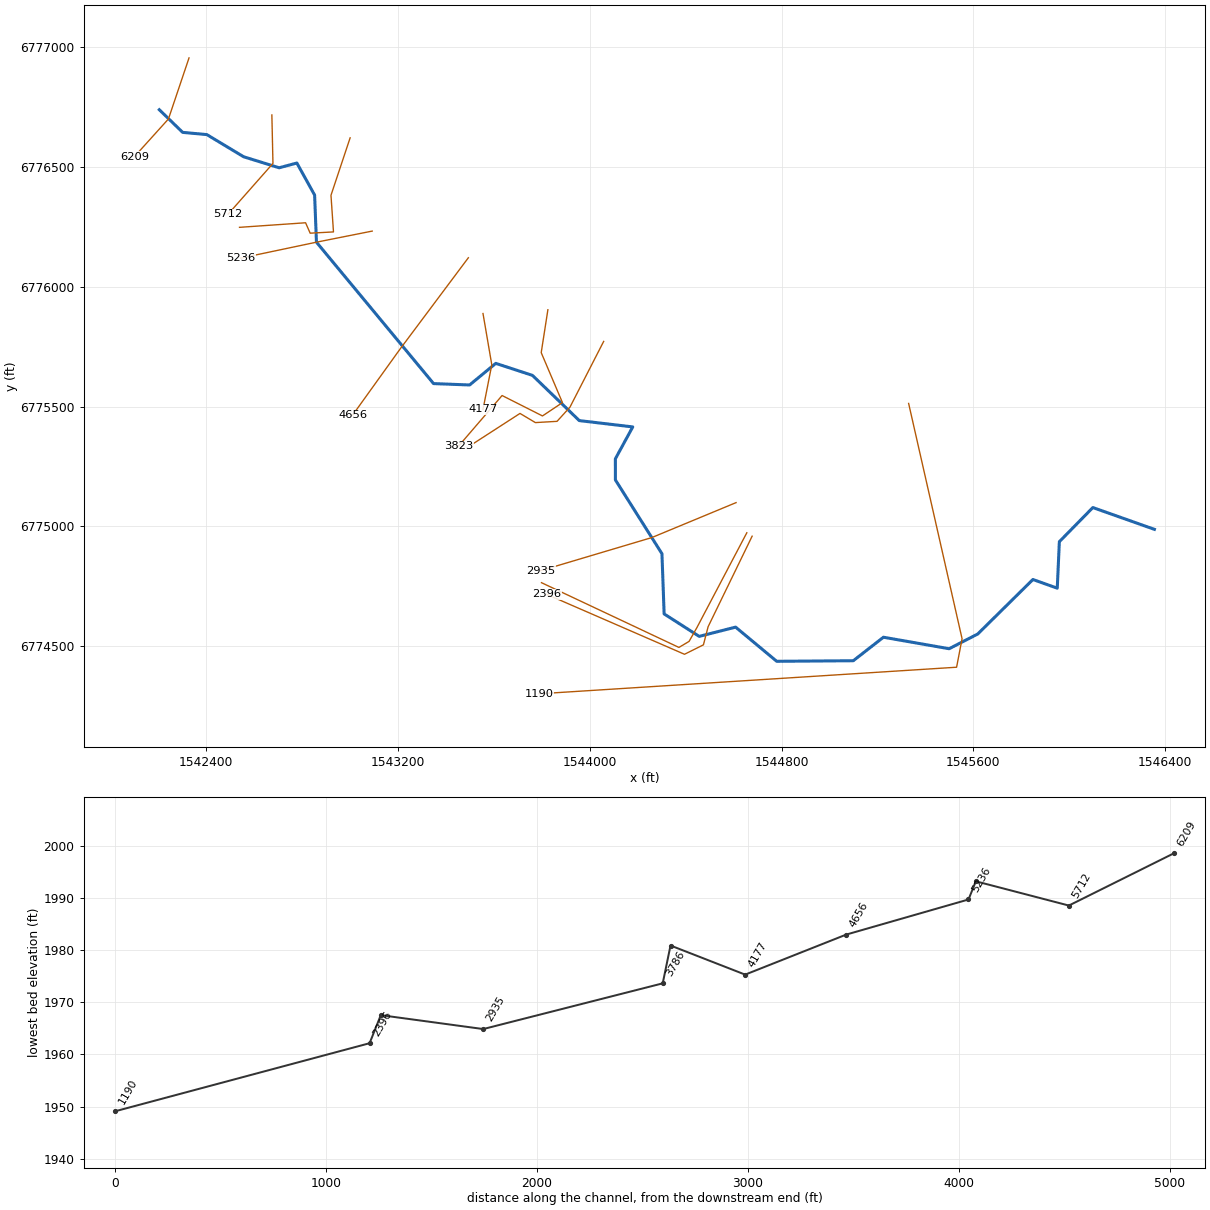
--- Elm 95.prj (project) ---

Proj Title=Elm 95 Base Level Engineering
Current Plan=p01
Default Exp/Contr=0.3,0.1
English Units
Geom File=g01
Flow File=f01
Plan File=p01
BEGIN DESCRIPTION:
Elm 95
END DESCRIPTION:

--- Elm 95.p01 (plan) ---

Plan Title=Multiple Run
Short Identifier=Multiple
Geom File=g01
Flow File=f01
Subcritical Flow
K Sum by GR= 0
Std Step Tol= 0.01
Critical Tol= 0.01
Num of Std Step Trials= 20
Max Error Tol= 0.3
Flow Tol Ratio= 0.001
Split Flow NTrial= 30
Split Flow Tol= 0.02
Split Flow Ratio= 0.02
Log Output Level= 0
Friction Slope Method= 1
Unsteady Friction Slope Method= 2
Unsteady Bridges Friction Slope Method= 1
Parabolic Critical Depth
Global Vel Dist=  1 , 1 , 1
Global Log Level= 0
CheckData=True
Encroach Param= -1, 0, 0, 0
BEGIN DESCRIPTION:
Multiple Run
END DESCRIPTION:

--- Elm 95.f01 (steady flow) ---

Flow Title=Multiple
Number of Profiles=7
Profile Names=10-year,25-year,50-year,1pct_min,100-year,1pct_plu,500-year
River Rch & RM= Elm 95,Reach-1,6209
     120     159     189     140     225     309     321
Boundary for River Rch & Prof#=Elm 95,Reach-1,1
Up Type=0
Dn Type=3
Dn Slope=0.005
Boundary for River Rch & Prof#=Elm 95,Reach-1,2
Up Type=0
Dn Type=3
Dn Slope=0.005
Boundary for River Rch & Prof#=Elm 95,Reach-1,3
Up Type=0
Dn Type=3
Dn Slope=0.005
Boundary for River Rch & Prof#=Elm 95,Reach-1,4
Up Type=0
Dn Type=3
Dn Slope=0.005
Boundary for River Rch & Prof#=Elm 95,Reach-1,5
Up Type=0
Dn Type=3
Dn Slope=0.005
Boundary for River Rch & Prof#=Elm 95,Reach-1,6
Up Type=0
Dn Type=3
Dn Slope=0.005
Boundary for River Rch & Prof#=Elm 95,Reach-1,7
Up Type=0
Dn Type=3
Dn Slope=0.005

--- Elm 95.g01 (geometry) ---

Geom Title=Existing Conditions

River Reach=Elm 95,Reach-1
Reach XY= 30
      1542205.00      6776738.00      1542302.55      6776643.46
      1542403.41      6776634.17      1542556.59      6776541.82
      1542705.11      6776495.81      1542778.71      6776515.64
      1542852.76      6776382.07      1542860.46      6776185.55
      1543348.81      6775595.81      1543499.14      6775590.06
      1543608.22      6775680.12      1543761.17      6775630.14
      1543956.46      6775441.54      1544179.53      6775415.14
      1544106.98      6775282.11      1544107.14      6775193.97
      1544301.25      6774886.45      1544310.36      6774635.30
      1544456.58      6774541.68      1544608.42      6774580.20
      1544779.88      6774437.70      1545099.14      6774440.07
      1545224.99      6774538.06      1545499.03      6774490.14
      1545618.22      6774551.62      1545848.29      6774778.84
      1545949.82      6774742.62      1545958.54      6774936.54
      1546098.26      6775078.87      1546355.00      6774988.00

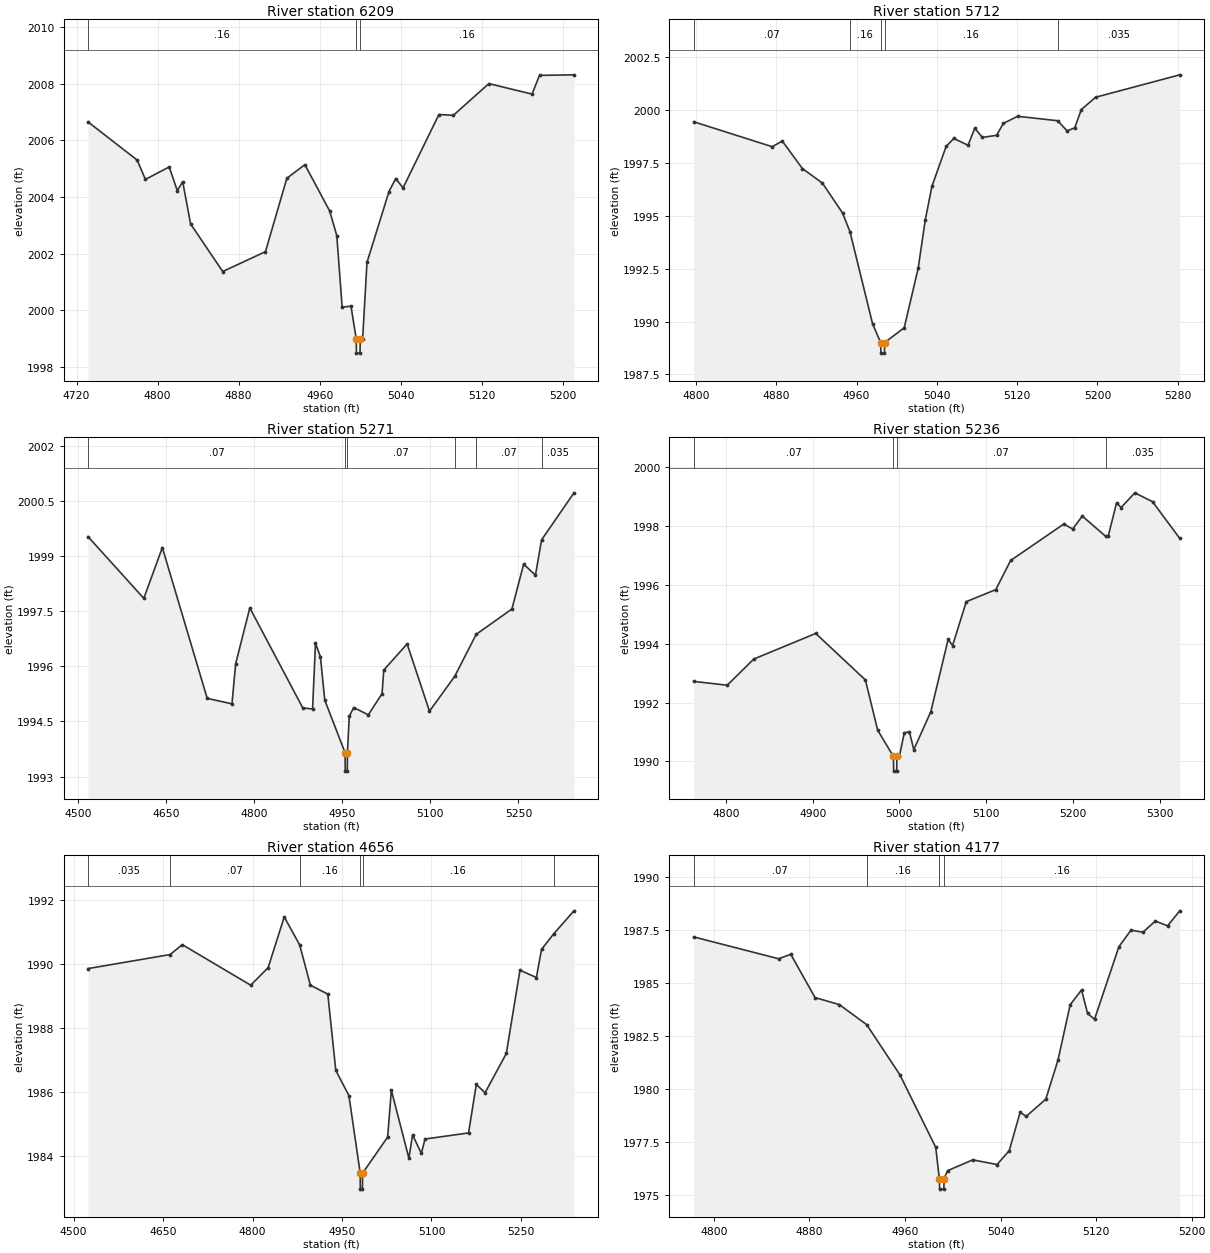
Type RM Length L Ch R = 1,6209,497,497,497
BEGIN DESCRIPTION:
450
END DESCRIPTION:
XS GIS Cut Line= 3
      1542329.03      6776954.01      1542243.22      6776699.38
      1542101.80      6776542.79
#Sta/Elev= 30
  4731.3 2006.65  4779.9 2005.30  4788.0 2004.62  4811.5 2005.06  4819.5 2004.22
  4824.8 2004.54  4832.6 2003.05  4864.3 2001.37  4906.5 2002.07  4927.6 2004.66
  4945.4 2005.14  4969.8 2003.51  4976.9 2002.64  4982.2 2000.11  4990.9 2000.15
  4996.1 1998.99  4996.3 1998.49  4999.8 1998.49  5000.1 1998.99  5002.4 1998.99
  5006.7 2001.69  5028.4 2004.19  5035.1 2004.65  5042.3 2004.32  5077.7 2006.91
  5091.9 2006.88  5127.0 2008.00  5169.6 2007.63  5177.0 2008.29  5211.0 2008.31
#Mann=3,-1,0
  4731.3    0.16       0  4996.1    0.07       0  5000.1    0.16       0
Bank Sta=4996.1,5000.1
Exp/Cntr=0.3,0.1

Type RM Length L Ch R = 1,5712,441,441,441
BEGIN DESCRIPTION:
449
END DESCRIPTION:
XS GIS Cut Line= 3
      1542674.52      6776716.18      1542679.04      6776514.03
      1542492.37      6776302.66
#Sta/Elev= 30
  4797.8 1999.45  4876.0 1998.27  4886.0 1998.54  4906.0 1997.24  4926.0 1996.55
  4946.0 1995.14  4953.4 1994.26  4976.0 1989.89  4984.0 1989.01  4984.3 1988.51
  4987.8 1988.51  4988.0 1989.01  5007.5 1989.71  5021.4 1992.52  5028.4 1994.79
  5035.1 1996.40  5049.3 1998.29  5056.9 1998.66  5071.1 1998.34  5077.8 1999.15
  5085.3 1998.71  5099.5 1998.81  5106.2 1999.37  5120.4 1999.71  5160.3 1999.50
  5169.8 1999.02  5177.3 1999.16  5184.0 2000.03  5198.2 2000.61  5282.0 2001.67
#Mann=5,-1,0
  4797.8    0.07       0  4953.4    0.16       0  4984.0    0.07       0
  4988.0    0.16       0  5160.3   0.035       0
Bank Sta=4984,4988
Exp/Cntr=0.3,0.1

Type RM Length L Ch R = 1,5271,35,35,35
BEGIN DESCRIPTION:
819
END DESCRIPTION:
XS GIS Cut Line= 6
      1543000.92      6776620.72      1542921.05      6776381.11
      1542931.46      6776228.33      1542834.24      6776223.12
      1542815.14      6776266.53      1542539.52      6776247.46
#Sta/Elev= 30
  4516.7 1999.53  4611.8 1997.85  4643.4 1999.23  4719.8 1995.13  4762.0 1994.98
  4768.3 1996.07  4792.4 1997.59  4882.6 1994.87  4899.3 1994.84  4904.3 1996.63
  4912.7 1996.26  4920.1 1995.08  4954.7 1993.65  4955.0 1993.15  4958.5 1993.15
  4958.7 1993.65  4961.8 1994.64  4969.4 1994.88  4994.3 1994.68  5017.7 1995.26
  5020.6 1995.90  5060.4 1996.61  5098.5 1994.78  5141.5 1995.73  5178.0 1996.87
  5238.9 1997.56  5258.9 1998.78  5279.0 1998.48  5289.4 1999.44  5344.6 2000.72
#Mann=6,-1,0
  4516.7    0.07       0  4954.7    0.07       0  4958.7    0.07       0
  5141.5    0.16       0  5178.0    0.07       0  5289.4   0.035       0
Bank Sta=4954.7,4958.7
Exp/Cntr=0.3,0.1

Type RM Length L Ch R = 1,5236,580,580,580
BEGIN DESCRIPTION:
448
END DESCRIPTION:
XS GIS Cut Line= 3
      1543092.90      6776231.80      1542860.46      6776185.55
      1542544.30      6776118.95
#Sta/Elev= 30
  4763.0 1992.72  4801.6 1992.59  4832.2 1993.48  4903.6 1994.35  4960.8 1992.77
  4975.0 1991.06  4993.1 1990.17  4993.4 1989.67  4996.9 1989.67  4997.1 1990.17
  5000.0 1990.17  5005.6 1990.97  5011.5 1991.01  5016.6 1990.40  5036.2 1991.69
  5056.2 1994.15  5061.3 1993.94  5077.1 1995.43  5111.1 1995.84  5128.2 1996.83
  5189.5 1998.07  5199.7 1997.90  5210.8 1998.34  5237.8 1997.65  5240.6 1997.65
  5250.3 1998.79  5255.5 1998.63  5271.3 1999.13  5291.7 1998.83  5323.1 1997.58
#Mann=4,-1,0
  4763.0    0.07       0  4993.1    0.07       0  4997.1    0.07       0
  5237.8   0.035       0
Bank Sta=4993.1,4997.1
Exp/Cntr=0.3,0.1

Type RM Length L Ch R = 1,4656,479,479,479
BEGIN DESCRIPTION:
447
END DESCRIPTION:
XS GIS Cut Line= 3
      1543493.95      6776120.67      1543208.98      6775739.65
      1543011.34      6775464.46
#Sta/Elev= 30
  4524.2 1989.86  4661.9 1990.30  4682.3 1990.61  4797.0 1989.34  4826.2 1989.89
  4853.2 1991.48  4879.1 1990.60  4897.0 1989.34  4926.2 1989.06  4939.6 1986.67
  4961.6 1985.88  4980.5 1983.45  4980.7 1982.95  4984.2 1982.95  4984.5 1983.45
  5026.5 1984.58  5032.7 1986.05  5062.1 1983.92  5068.3 1984.65  5083.0 1984.07
  5089.2 1984.52  5162.1 1984.71  5175.1 1986.23  5189.8 1985.97  5225.4 1987.20
  5248.3 1989.81  5275.8 1989.58  5284.4 1990.46  5304.9 1990.95  5338.8 1991.67
#Mann=6,-1,0
  4524.2   0.035       0  4661.9    0.07       0  4879.1    0.16       0
  4980.5    0.07       0  4984.5    0.16       0  5304.9    0.07       0
Bank Sta=4980.5,4984.5
Exp/Cntr=0.3,0.1

Type RM Length L Ch R = 1,4177,354,354,354
BEGIN DESCRIPTION:
446
END DESCRIPTION:
XS GIS Cut Line= 3
      1543555.00      6775888.02      1543591.63      6775674.44
      1543555.00      6775488.01
#Sta/Elev= 30
  4783.3 1987.18  4854.3 1986.15  4864.5 1986.36  4884.8 1984.32  4905.1 1983.99
  4928.1 1983.04  4955.8 1980.68  4985.8 1977.26  4988.8 1975.79  4989.1 1975.29
  4992.6 1975.29  4992.8 1975.79  4995.7 1976.16  5016.8 1976.67  5037.1 1976.45
  5047.3 1977.10  5056.4 1978.91  5061.5 1978.72  5077.9 1979.53  5088.1 1981.37
  5098.3 1983.98  5107.8 1984.68  5112.9 1983.57  5118.7 1983.30  5139.1 1986.72
  5149.2 1987.50  5159.2 1987.40  5169.6 1987.93  5179.8 1987.70  5190.0 1988.41
#Mann=4,-1,0
  4783.3    0.07       0  4928.1    0.16       0  4988.8    0.07       0
  4992.8    0.16       0
Bank Sta=4988.8,4992.8
Exp/Cntr=0.3,0.1

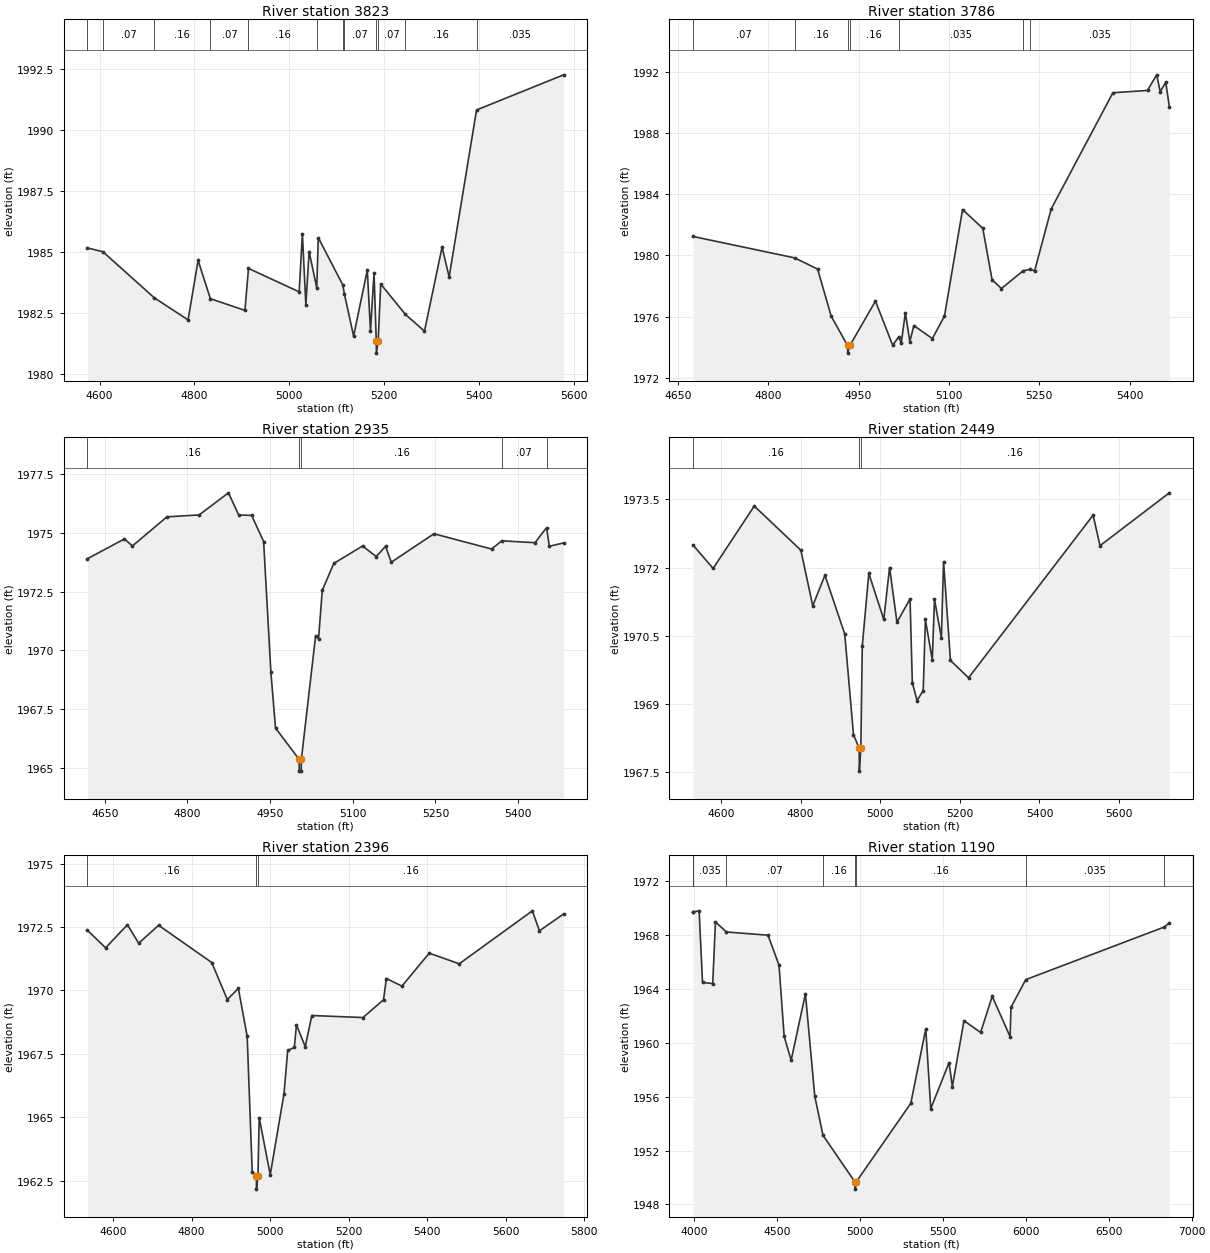
Type RM Length L Ch R = 1,3823,37,37,37
BEGIN DESCRIPTION:
817
END DESCRIPTION:
XS GIS Cut Line= 6
      1543825.57      6775903.72      1543797.78      6775724.86
      1543886.33      6775516.53      1543802.99      6775460.97
      1543634.59      6775546.04      1543452.26      6775334.21
#Sta/Elev= 30
  4574.3 1985.17  4607.0 1985.01  4715.0 1983.13  4786.5 1982.22  4807.6 1984.66
  4833.5 1983.09  4906.4 1982.61  4913.9 1984.33  5020.8 1983.37  5027.6 1985.75
  5034.9 1982.83  5041.8 1985.02  5057.9 1983.53  5061.1 1985.59  5112.9 1983.65
  5116.0 1983.30  5135.6 1981.56  5164.5 1984.26  5171.2 1981.76  5178.7 1984.14
  5183.4 1981.36  5183.7 1980.86  5187.4 1981.36  5192.8 1983.69  5244.7 1982.45
  5285.1 1981.76  5322.2 1985.20  5337.1 1983.98  5394.9 1990.82  5578.7 1992.26
#Mann=12,-1,0
  4574.3    0.16       0  4607.0    0.07       0  4715.0    0.16       0
  4833.5    0.07       0  4913.9    0.16       0  5057.9   0.035       0
  5112.9    0.16       0  5116.0    0.07       0  5183.4    0.07       0
  5187.4    0.07       0  5244.7    0.16       0  5394.9   0.035       0
Bank Sta=5183.4,5187.4
Exp/Cntr=0.3,0.1

Type RM Length L Ch R = 1,3786,851,851,851
BEGIN DESCRIPTION:
818
END DESCRIPTION:
XS GIS Cut Line= 6
      1544058.22      6775771.78      1543917.58      6775497.43
      1543863.76      6775438.40      1543773.48      6775433.19
      1543709.24      6775471.39      1543510.34      6775342.78
#Sta/Elev= 30
  4675.6 1981.24  4844.1 1979.84  4882.1 1979.11  4904.6 1976.04  4931.7 1974.12
  4932.0 1973.62  4935.7 1974.12  4978.1 1977.02  5006.7 1974.13  5016.5 1974.68
  5020.9 1974.28  5027.7 1976.26  5035.1 1974.37  5041.8 1975.42  5072.5 1974.57
  5092.6 1976.04  5122.6 1983.00  5156.2 1981.77  5171.6 1978.41  5187.2 1977.84
  5223.1 1979.00  5235.0 1979.09  5242.2 1979.00  5269.7 1983.04  5372.1 1990.63
  5429.5 1990.78  5444.7 1991.80  5450.6 1990.70  5459.8 1991.31  5465.8 1989.71
#Mann=7,-1,0
  4675.6    0.07       0  4844.1    0.16       0  4931.7    0.07       0
  4935.7    0.16       0  5016.5   0.035       0  5223.1    0.07       0
  5235.0   0.035       0
Bank Sta=4931.7,4935.7
Exp/Cntr=0.3,0.1

Type RM Length L Ch R = 1,2935,486,486,486
BEGIN DESCRIPTION:
814
END DESCRIPTION:
XS GIS Cut Line= 3
      1544610.28      6775099.42      1544258.72      6774953.59
      1543795.14      6774815.56
#Sta/Elev= 30
  4618.5 1973.90  4685.6 1974.74  4700.0 1974.44  4762.7 1975.68  4821.2 1975.76
  4874.4 1976.70  4892.9 1975.76  4916.5 1975.74  4938.2 1974.63  4951.4 1969.07
  4959.8 1966.70  5002.7 1965.37  5002.9 1964.87  5006.4 1964.87  5006.7 1965.37
  5032.6 1970.63  5037.9 1970.50  5044.7 1972.56  5065.6 1973.70  5117.8 1974.44
  5142.6 1973.99  5159.5 1974.43  5169.9 1973.75  5247.3 1974.96  5352.1 1974.31
  5370.3 1974.66  5430.8 1974.58  5451.7 1975.22  5456.8 1974.43  5482.8 1974.57
#Mann=5,-1,0
  4618.5    0.16       0  5002.7    0.07       0  5006.7    0.16       0
  5370.3    0.07       0  5451.7    0.16       0
Bank Sta=5002.7,5006.7
Exp/Cntr=0.3,0.1

Type RM Length L Ch R = 1,2449,53,53,53
BEGIN DESCRIPTION:
815
END DESCRIPTION:
XS GIS Cut Line= 5
      1544655.19      6774973.74      1544446.87      6774577.94
      1544414.32      6774520.65      1544372.06      6774495.57
      1543798.88      6774765.57
#Sta/Elev= 30
  4530.4 1972.49  4580.5 1971.98  4683.8 1973.35  4800.8 1972.38  4830.7 1971.16
  4861.3 1971.83  4911.0 1970.54  4933.0 1968.33  4947.4 1968.03  4947.7 1967.53
  4951.4 1968.03  4955.1 1970.28  4971.5 1971.87  5009.1 1970.86  5023.6 1972.00
  5042.2 1970.80  5075.0 1971.31  5080.8 1969.47  5092.7 1969.08  5108.1 1969.30
  5113.6 1970.86  5130.9 1969.97  5136.4 1971.30  5153.7 1970.46  5159.2 1972.13
  5176.5 1969.96  5222.0 1969.58  5534.8 1973.15  5552.1 1972.48  5726.3 1973.64
#Mann=3,-1,0
  4530.4    0.16       0  4947.4    0.07       0  4951.4    0.16       0
Bank Sta=4947.4,4951.4
Exp/Cntr=0.3,0.1

Type RM Length L Ch R = 1,2396,1206,1206,1206
BEGIN DESCRIPTION:
816
END DESCRIPTION:
XS GIS Cut Line= 5
      1544677.35      6774959.48      1544493.75      6774581.85
      1544474.22      6774506.33      1544395.25      6774466.99
      1543821.20      6774716.62
#Sta/Elev= 30
  4535.1 1972.37  4581.2 1971.68  4636.8 1972.59  4665.4 1971.86  4716.1 1972.57
  4851.4 1971.10  4891.0 1969.64  4919.1 1970.08  4941.6 1968.19  4954.4 1962.85
  4965.0 1962.66  4965.3 1962.16  4969.0 1962.66  4972.2 1964.98  5000.3 1962.73
  5035.4 1965.93  5044.7 1967.63  5061.5 1967.75  5067.1 1968.64  5089.4 1967.78
  5106.2 1969.01  5236.3 1968.93  5288.6 1969.63  5296.0 1970.47  5335.5 1970.17
  5405.0 1971.47  5481.3 1971.05  5667.5 1973.14  5685.5 1972.35  5747.2 1973.02
#Mann=3,-1,0
  4535.1    0.16       0  4965.0    0.07       0  4969.0    0.16       0
Bank Sta=4965,4969
Exp/Cntr=0.3,0.1

Type RM Length L Ch R = 1,1190,0,0,0
BEGIN DESCRIPTION:
445
END DESCRIPTION:
XS GIS Cut Line= 4
      1545330.01      6775512.97      1545552.83      6774531.85
      1545530.00      6774413.00      1543788.95      6774302.17
#Sta/Elev= 30
  3993.9 1969.71  3994.4 1969.73  4029.8 1969.81  4050.3 1964.49  4111.8 1964.41
  4128.3 1968.99  4194.1 1968.24  4445.2 1968.00  4511.7 1965.77  4542.5 1960.49
  4584.7 1958.71  4670.9 1963.65  4727.1 1956.05  4776.6 1953.14  4971.2 1949.64
  4971.4 1949.14  4975.2 1949.64  5306.4 1955.52  5396.6 1961.05  5426.6 1955.12
  5536.9 1958.53  5556.9 1956.76  5627.0 1961.65  5727.3 1960.78  5797.4 1963.46
  5905.3 1960.46  5910.3 1962.64  5999.5 1964.70  6835.2 1968.61  6865.6 1968.92
#Mann=8,-1,0
  3993.9    0.07       0  3994.4   0.035       0  4194.1    0.07       0
  4776.6    0.16       0  4971.2    0.07       0  4975.2    0.16       0
  5999.5   0.035       0  6835.2    0.16       0
Bank Sta=4971.2,4975.2
Exp/Cntr=0.3,0.1

Chan Stop Cuts=-1