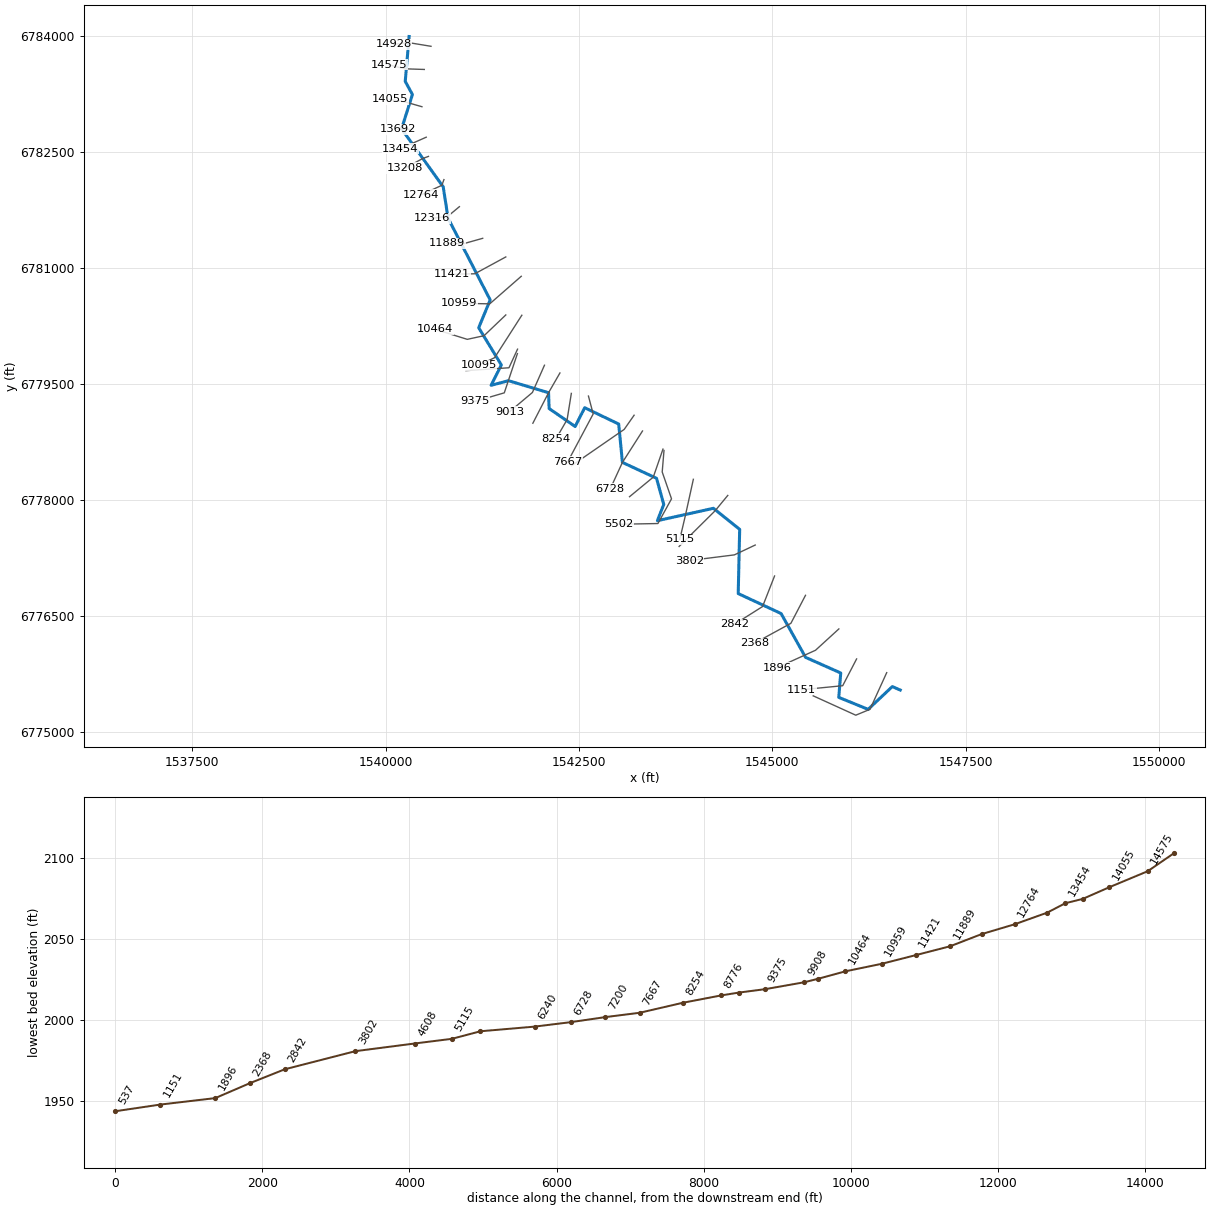
--- Elm 96.prj (project) ---

Proj Title=Elm 96 Base Level Engineering
Current Plan=p01
Default Exp/Contr=0.3,0.1
English Units
Geom File=g01
Flow File=f01
Plan File=p01
BEGIN DESCRIPTION:
Elm 96
END DESCRIPTION:

--- Elm 96.p01 (plan) ---

Plan Title=Multiple Run
Short Identifier=Multiple
Geom File=g01
Flow File=f01
Subcritical Flow
K Sum by GR= 0
Std Step Tol= 0.01
Critical Tol= 0.01
Num of Std Step Trials= 20
Max Error Tol= 0.3
Flow Tol Ratio= 0.001
Split Flow NTrial= 30
Split Flow Tol= 0.02
Split Flow Ratio= 0.02
Log Output Level= 0
Friction Slope Method= 1
Unsteady Friction Slope Method= 2
Unsteady Bridges Friction Slope Method= 1
Parabolic Critical Depth
Global Vel Dist=  1 , 1 , 1
Global Log Level= 0
CheckData=True
Encroach Param= -1, 0, 0, 0
BEGIN DESCRIPTION:
Multiple Run
END DESCRIPTION:

--- Elm 96.f01 (steady flow) ---

Flow Title=Multiple
Number of Profiles=7
Profile Names=10-year,25-year,50-year,1pct_min,100-year,1pct_plu,500-year
River Rch & RM= Elm 96,Reach-1,14928
     263     372     466     363     582     801     916
River Rch & RM= Elm 96,Reach-1,11889
     418     600     757     592     948    1310    1510
Boundary for River Rch & Prof#=Elm 96,Reach-1,1
Up Type=0
Dn Type=3
Dn Slope=0.005
Boundary for River Rch & Prof#=Elm 96,Reach-1,2
Up Type=0
Dn Type=3
Dn Slope=0.005
Boundary for River Rch & Prof#=Elm 96,Reach-1,3
Up Type=0
Dn Type=3
Dn Slope=0.005
Boundary for River Rch & Prof#=Elm 96,Reach-1,4
Up Type=0
Dn Type=3
Dn Slope=0.005
Boundary for River Rch & Prof#=Elm 96,Reach-1,5
Up Type=0
Dn Type=3
Dn Slope=0.005
Boundary for River Rch & Prof#=Elm 96,Reach-1,6
Up Type=0
Dn Type=3
Dn Slope=0.005
Boundary for River Rch & Prof#=Elm 96,Reach-1,7
Up Type=0
Dn Type=3
Dn Slope=0.005

--- Elm 96.g01 (geometry) ---

Geom Title=Existing Conditions

River Reach=Elm 96,Reach-1
Reach XY= 30
      1540305.00      6783988.00      1540254.78      6783408.20
      1540347.70      6783237.92      1540207.24      6782793.93
      1540745.70      6782044.67      1540808.54      6781639.47
      1541353.24      6780581.88      1541204.50      6780222.80
      1541497.40      6779741.34      1541365.06      6779477.88
      1541589.59      6779537.98      1542107.98      6779382.61
      1542115.28      6779177.84      1542451.87      6778945.50
      1542575.04      6779188.52      1543014.83      6778977.48
      1543062.86      6778481.20      1543503.82      6778275.98
      1543597.47      6777937.99      1543515.03      6777727.93
      1544239.67      6777888.05      1544579.02      6777615.33
      1544560.09      6776785.70      1545114.68      6776527.25
      1545431.10      6775960.72      1545885.77      6775758.57
      1545860.18      6775443.44      1546239.84      6775288.36
      1546552.66      6775582.93      1546655.00      6775538.00

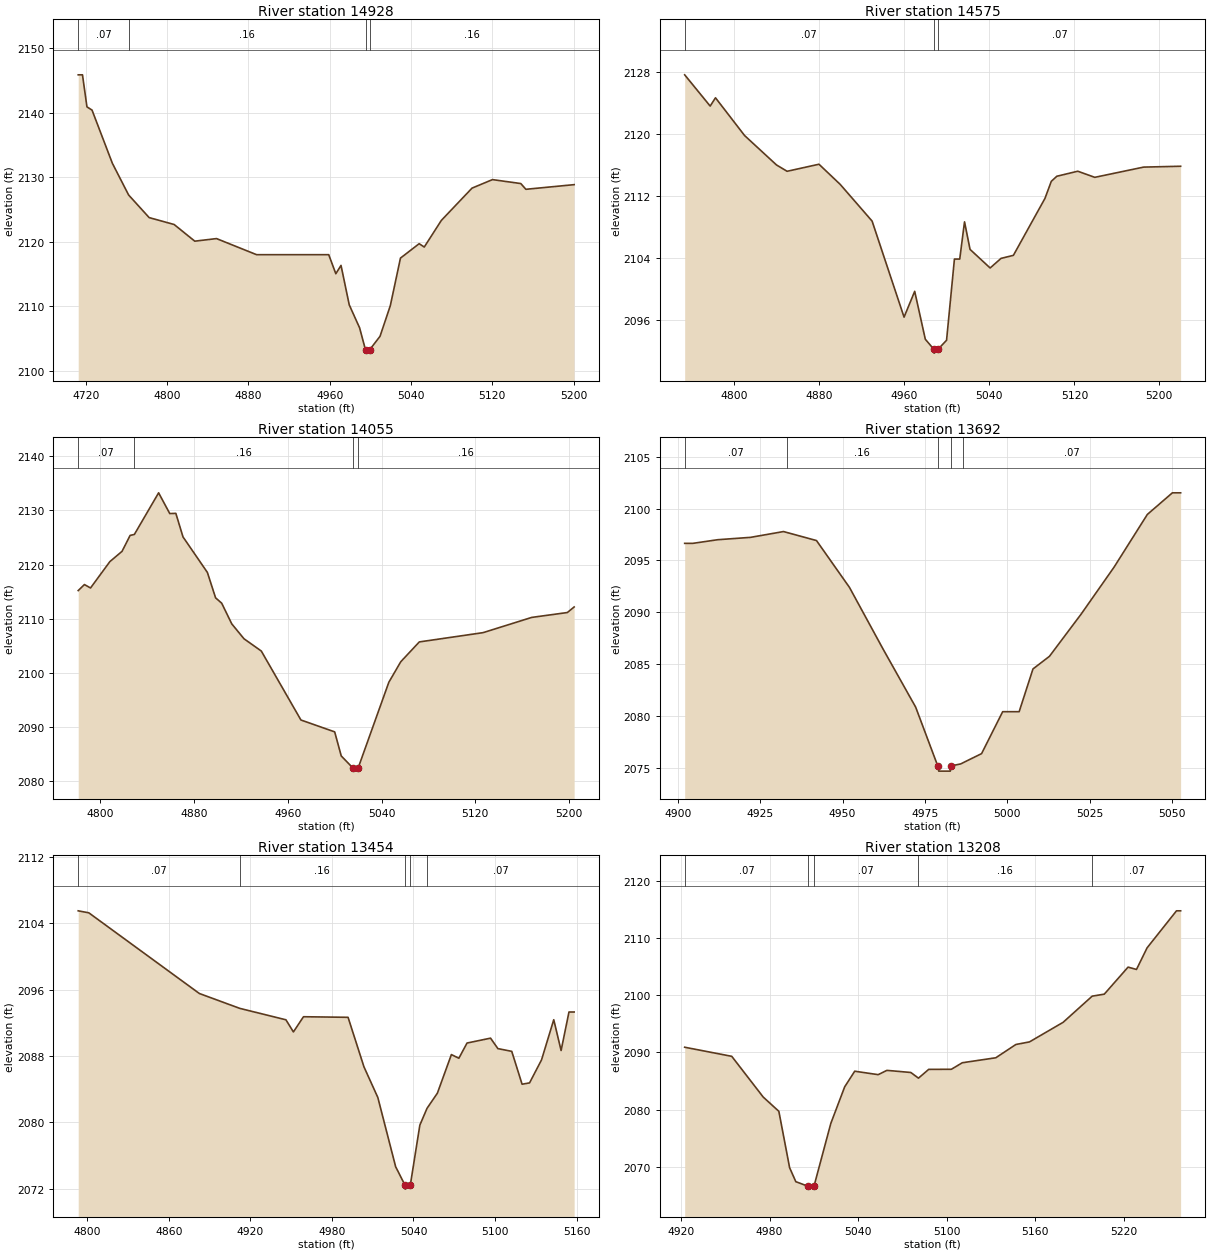
Type RM Length L Ch R = 1,14928,353,353,353
BEGIN DESCRIPTION:
308
END DESCRIPTION:
XS GIS Cut Line= 3
      1540588.19      6783861.57      1540304.59      6783908.17
      1540105.01      6783888.00
#Sta/Elev= 30
  4712.6 2145.84  4716.8 2145.84  4721.2 2140.88  4726.2 2140.38  4746.2 2132.15
  4762.2 2127.24  4782.4 2123.74  4807.0 2122.67  4827.3 2120.09  4848.7 2120.49
  4888.1 2118.00  4959.1 2118.00  4966.1 2115.05  4971.2 2116.34  4979.3 2110.23
  4989.5 2106.67  4995.3 2103.26  4995.5 2102.76  4999.3 2103.26  5009.6 2105.37
  5019.7 2110.10  5029.7 2117.47  5048.1 2119.70  5053.1 2119.18  5069.9 2123.30
  5100.1 2128.30  5120.2 2129.62  5148.1 2129.01  5153.1 2128.12  5200.6 2128.84
#Mann=4,-1,0
  4712.6    0.07       0  4762.2    0.16       0  4995.3    0.07       0
  4999.3    0.16       0
Bank Sta=4995.3,4999.3
Exp/Cntr=0.3,0.1

Type RM Length L Ch R = 1,14575,520,520,520
BEGIN DESCRIPTION:
823
END DESCRIPTION:
XS GIS Cut Line= 3
      1540501.34      6783562.10      1540245.27      6783570.78
      1540041.23      6783622.87
#Sta/Elev= 30
  4753.2 2127.64  4777.2 2123.61  4782.2 2124.68  4809.6 2119.81  4839.6 2116.02
  4849.6 2115.20  4879.6 2116.11  4899.6 2113.51  4929.6 2108.78  4959.7 2096.39
  4969.7 2099.72  4979.7 2093.54  4987.7 2092.25  4987.9 2091.75  4991.7 2092.25
  4999.7 2093.41  5007.1 2103.88  5012.1 2103.88  5016.6 2108.68  5021.8 2105.13
  5040.7 2102.73  5051.0 2103.97  5062.6 2104.36  5092.3 2111.70  5098.3 2113.91
  5103.5 2114.56  5123.2 2115.21  5139.2 2114.42  5185.2 2115.74  5220.0 2115.85
#Mann=3,-1,0
  4753.2    0.07       0  4987.7    0.07       0  4991.7    0.07       0
Bank Sta=4987.7,4991.7
Exp/Cntr=0.3,0.1

Type RM Length L Ch R = 1,14055,363,363,363
BEGIN DESCRIPTION:
307
END DESCRIPTION:
XS GIS Cut Line= 3
      1540470.94      6783080.34      1540260.55      6783140.43
      1540059.32      6783175.69
#Sta/Elev= 30
  4781.2 2115.20  4786.5 2116.31  4791.7 2115.68  4808.2 2120.54  4818.6 2122.44
  4825.5 2125.38  4829.1 2125.55  4849.8 2133.23  4859.3 2129.41  4864.5 2129.44
  4870.6 2125.10  4891.4 2118.55  4898.4 2113.86  4903.6 2112.88  4912.2 2109.06
  4922.6 2106.32  4937.4 2104.05  4971.2 2091.33  5000.0 2089.14  5005.6 2084.70
  5015.9 2082.40  5016.1 2081.90  5019.9 2082.40  5046.2 2098.29  5056.4 2102.08
  5072.2 2105.73  5126.6 2107.44  5168.1 2110.25  5198.5 2111.15  5204.3 2112.18
#Mann=4,-1,0
  4781.2    0.07       0  4829.1    0.16       0  5015.9    0.07       0
  5019.9    0.16       0
Bank Sta=5015.9,5019.9
Exp/Cntr=0.3,0.1

Type RM Length L Ch R = 1,13692,238,238,238
BEGIN DESCRIPTION:
306
END DESCRIPTION:
XS GIS Cut Line= 3
      1540304.96      6782788.00      1540207.24      6782793.93
      1540154.97      6782788.00
#Sta/Elev= 26
  4902.1 2096.65  4904.6 2096.65  4912.1 2097.00  4922.1 2097.23  4932.1 2097.79
  4933.0 2097.71  4942.1 2096.92  4952.1 2092.40  4962.2 2086.50  4972.2 2080.83
  4978.9 2075.15  4979.2 2074.65  4982.7 2074.65  4982.9 2075.15  4985.9 2075.35
  4986.7 2075.48  4992.2 2076.34  4998.6 2080.39  5003.6 2080.39  5007.8 2084.52
  5012.8 2085.74  5022.4 2089.81  5032.4 2094.35  5042.5 2099.44  5050.1 2101.53
  5052.6 2101.53
#Mann=5,-1,0
  4902.1    0.07       0  4933.0    0.16       0  4978.9    0.07       0
  4982.9    0.16       0  4986.7    0.07       0
Bank Sta=4978.9,4982.9
Exp/Cntr=0.3,0.1

Type RM Length L Ch R = 1,13454,246,246,246
BEGIN DESCRIPTION:
872
END DESCRIPTION:
XS GIS Cut Line= 2
      1540526.39      6782686.49      1540193.03      6782538.33
#Sta/Elev= 30
  4793.4 2105.48  4801.2 2105.24  4882.5 2095.52  4912.2 2093.73  4946.2 2092.35
  4951.7 2090.89  4959.1 2092.72  4991.9 2092.65  5003.6 2086.68  5013.8 2082.99
  5026.9 2074.65  5033.7 2072.45  5033.9 2071.95  5037.7 2072.45  5044.7 2079.66
  5050.0 2081.69  5057.6 2083.51  5067.9 2088.16  5073.4 2087.72  5079.4 2089.55
  5096.7 2090.14  5102.1 2088.88  5112.3 2088.55  5119.9 2084.59  5125.4 2084.75
  5134.2 2087.52  5143.2 2092.36  5148.6 2088.65  5154.4 2093.29  5158.2 2093.29
#Mann=5,-1,0
  4793.4    0.07       0  4912.2    0.16       0  5033.7    0.07       0
  5037.7    0.16       0  5050.0    0.07       0
Bank Sta=5033.7,5037.7
Exp/Cntr=0.3,0.1

Type RM Length L Ch R = 1,13208,444,444,444
BEGIN DESCRIPTION:
305
END DESCRIPTION:
XS GIS Cut Line= 3
      1540554.96      6782437.99      1540482.12      6782411.52
      1540255.03      6782288.02
#Sta/Elev= 30
  4922.5 2090.92  4954.4 2089.33  4975.7 2082.22  4986.3 2079.73  4993.6 2069.88
  4997.8 2067.44  5006.1 2066.64  5006.4 2066.14  5010.1 2066.64  5021.5 2077.61
  5030.9 2084.00  5037.7 2086.73  5053.6 2086.13  5059.5 2086.88  5075.7 2086.51
  5080.9 2085.52  5087.8 2087.05  5103.2 2087.07  5110.6 2088.21  5133.3 2089.08
  5146.9 2091.40  5156.1 2091.85  5178.9 2095.27  5198.6 2099.84  5206.8 2100.19
  5222.9 2104.91  5228.6 2104.50  5235.8 2108.28  5255.7 2114.74  5258.5 2114.74
#Mann=5,-1,0
  4922.5    0.07       0  5006.1    0.07       0  5010.1    0.07       0
  5080.9    0.16       0  5198.6    0.07       0
Bank Sta=5006.1,5010.1
Exp/Cntr=0.3,0.1

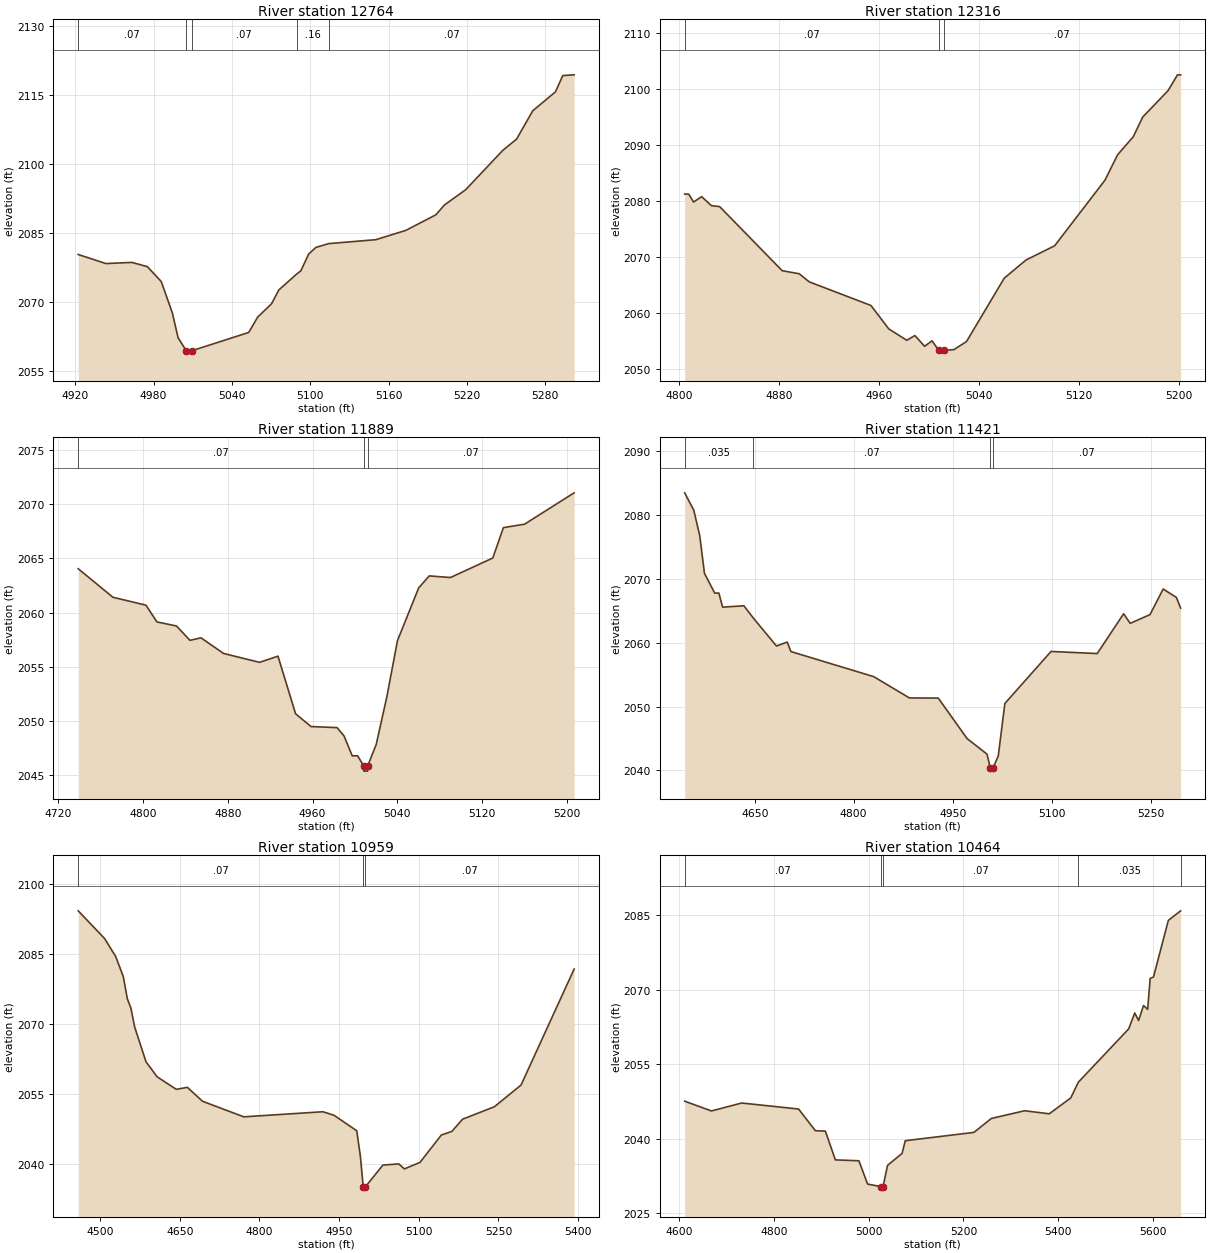
Type RM Length L Ch R = 1,12764,448,448,448
BEGIN DESCRIPTION:
304
END DESCRIPTION:
XS GIS Cut Line= 3
      1540754.99      6782137.97      1540729.23      6782064.67
      1540454.97      6781937.99
#Sta/Elev= 30
  4922.3 2080.34  4943.5 2078.37  4963.4 2078.62  4975.3 2077.69  4985.9 2074.47
  4994.4 2067.65  4998.8 2062.27  5005.1 2059.43  5005.3 2058.93  5009.1 2059.43
  5052.9 2063.42  5059.7 2066.74  5070.4 2069.65  5075.9 2072.63  5089.8 2076.14
  5092.8 2076.80  5098.8 2080.43  5104.3 2081.87  5114.2 2082.70  5150.2 2083.55
  5173.2 2085.57  5196.1 2088.93  5202.9 2091.11  5219.0 2094.39  5247.5 2102.95
  5258.0 2105.37  5270.4 2111.52  5287.8 2115.64  5293.4 2119.17  5302.1 2119.33
#Mann=5,-1,0
  4922.3    0.07       0  5005.1    0.07       0  5009.1    0.07       0
  5089.8    0.16       0  5114.2    0.07       0
Bank Sta=5005.1,5009.1
Exp/Cntr=0.3,0.1

Type RM Length L Ch R = 1,12316,427,427,427
BEGIN DESCRIPTION:
303
END DESCRIPTION:
XS GIS Cut Line= 3
      1540954.97      6781787.98      1540804.73      6781662.89
      1540604.97      6781638.00
#Sta/Elev= 30
  4804.5 2081.30  4807.7 2081.30  4811.6 2079.88  4818.1 2080.84  4825.9 2079.23
  4832.5 2079.06  4882.5 2067.61  4896.2 2067.06  4904.1 2065.62  4953.5 2061.40
  4967.8 2057.21  4982.2 2055.18  4988.7 2056.02  4996.5 2054.10  5002.4 2055.08
  5007.8 2053.38  5008.1 2052.88  5011.8 2053.38  5019.9 2053.50  5030.0 2054.95
  5060.2 2066.28  5077.6 2069.52  5100.5 2072.06  5140.8 2083.79  5150.9 2088.33
  5163.4 2091.54  5171.0 2095.07  5191.2 2099.77  5198.8 2102.61  5201.3 2102.61
#Mann=3,-1,0
  4804.5    0.07       0  5007.8    0.07       0  5011.8    0.07       0
Bank Sta=5007.8,5011.8
Exp/Cntr=0.3,0.1

Type RM Length L Ch R = 1,11889,468,468,468
BEGIN DESCRIPTION:
302
END DESCRIPTION:
XS GIS Cut Line= 3
      1541256.55      6781378.94      1541005.15      6781308.06
      1540798.23      6781313.79
#Sta/Elev= 30
  4738.8 2064.04  4771.6 2061.41  4802.8 2060.68  4813.1 2059.14  4831.6 2058.76
  4844.3 2057.44  4854.7 2057.67  4876.0 2056.23  4910.0 2055.41  4927.4 2055.98
  4944.0 2050.67  4958.6 2049.49  4983.2 2049.39  4989.8 2048.62  4997.5 2046.79
  5002.6 2046.79  5008.2 2045.88  5008.4 2045.38  5011.9 2045.38  5012.2 2045.88
  5020.2 2047.86  5030.2 2052.25  5040.2 2057.41  5060.2 2062.27  5070.2 2063.38
  5090.2 2063.23  5130.2 2065.03  5140.2 2067.83  5160.2 2068.15  5207.0 2071.04
#Mann=3,-1,0
  4738.8    0.07       0  5008.2    0.07       0  5012.2    0.07       0
Bank Sta=5008.2,5012.2
Exp/Cntr=0.3,0.1

Type RM Length L Ch R = 1,11421,462,462,462
BEGIN DESCRIPTION:
301
END DESCRIPTION:
XS GIS Cut Line= 3
      1541555.03      6781138.01      1541154.17      6780920.22
      1540858.62      6780914.56
#Sta/Elev= 30
  4543.8 2083.47  4557.6 2080.75  4566.6 2076.78  4573.8 2070.86  4589.4 2067.76
  4595.6 2067.78  4601.3 2065.57  4633.6 2065.78  4647.3 2063.93  4683.0 2059.48
  4699.2 2060.10  4704.9 2058.61  4830.3 2054.69  4884.5 2051.35  4928.2 2051.33
  4971.9 2044.99  5002.1 2042.55  5007.1 2040.39  5007.4 2039.89  5011.2 2040.39
  5019.2 2042.28  5029.2 2050.49  5099.2 2058.63  5169.2 2058.30  5209.2 2064.53
  5219.2 2063.03  5249.2 2064.40  5269.2 2068.41  5289.2 2067.09  5295.6 2065.42
#Mann=4,-1,0
  4543.8   0.035       0  4647.3    0.07       0  5007.1    0.07       0
  5011.2    0.07       0
Bank Sta=5007.1,5011.2
Exp/Cntr=0.3,0.1

Type RM Length L Ch R = 1,10959,495,495,495
BEGIN DESCRIPTION:
300
END DESCRIPTION:
XS GIS Cut Line= 3
      1541754.98      6780887.98      1541347.52      6780531.94
      1540954.97      6780538.00
#Sta/Elev= 30
  4458.9 2094.28  4508.7 2088.32  4529.6 2084.44  4543.8 2080.15  4551.4 2075.40
  4558.1 2073.41  4565.1 2069.38  4586.5 2061.89  4607.4 2058.66  4643.5 2055.96
  4664.4 2056.39  4692.9 2053.40  4770.7 2050.06  4919.7 2051.15  4940.6 2050.39
  4983.3 2047.07  4990.1 2041.63  4995.5 2035.04  4995.8 2034.54  4999.6 2035.04
  5032.5 2039.70  5062.5 2039.95  5073.0 2038.88  5102.5 2040.29  5142.5 2046.15
  5162.5 2046.94  5182.5 2049.55  5242.5 2052.23  5292.6 2056.88  5392.6 2081.78
#Mann=3,-1,0
  4458.9    0.07       0  4995.5    0.07       0  4999.6    0.07       0
Bank Sta=4995.5,4999.6
Exp/Cntr=0.3,0.1

Type RM Length L Ch R = 1,10464,369,369,369
BEGIN DESCRIPTION:
299
END DESCRIPTION:
XS GIS Cut Line= 4
      1541555.03      6780388.03      1541274.01      6780119.78
      1541056.90      6780072.52      1540640.26      6780202.71
#Sta/Elev= 30
  4611.5 2047.59  4668.0 2045.62  4731.8 2047.22  4852.0 2046.01  4887.5 2041.64
  4908.6 2041.56  4929.7 2035.77  4979.4 2035.59  4997.7 2030.90  5026.2 2030.38
  5026.4 2029.88  5030.3 2030.38  5039.9 2034.67  5070.6 2037.08  5077.3 2039.63
  5222.2 2041.30  5259.1 2044.11  5329.3 2045.66  5381.3 2045.05  5426.7 2048.24
  5442.8 2051.42  5549.0 2062.14  5561.9 2065.36  5569.9 2063.83  5580.4 2066.85
  5589.1 2066.09  5594.4 2072.31  5601.4 2072.59  5632.8 2084.00  5658.7 2085.92
#Mann=5,-1,0
  4611.5    0.07       0  5026.2    0.07       0  5030.3    0.07       0
  5442.8   0.035       0  5658.7    0.07       0
Bank Sta=5026.2,5030.3
Exp/Cntr=0.3,0.1

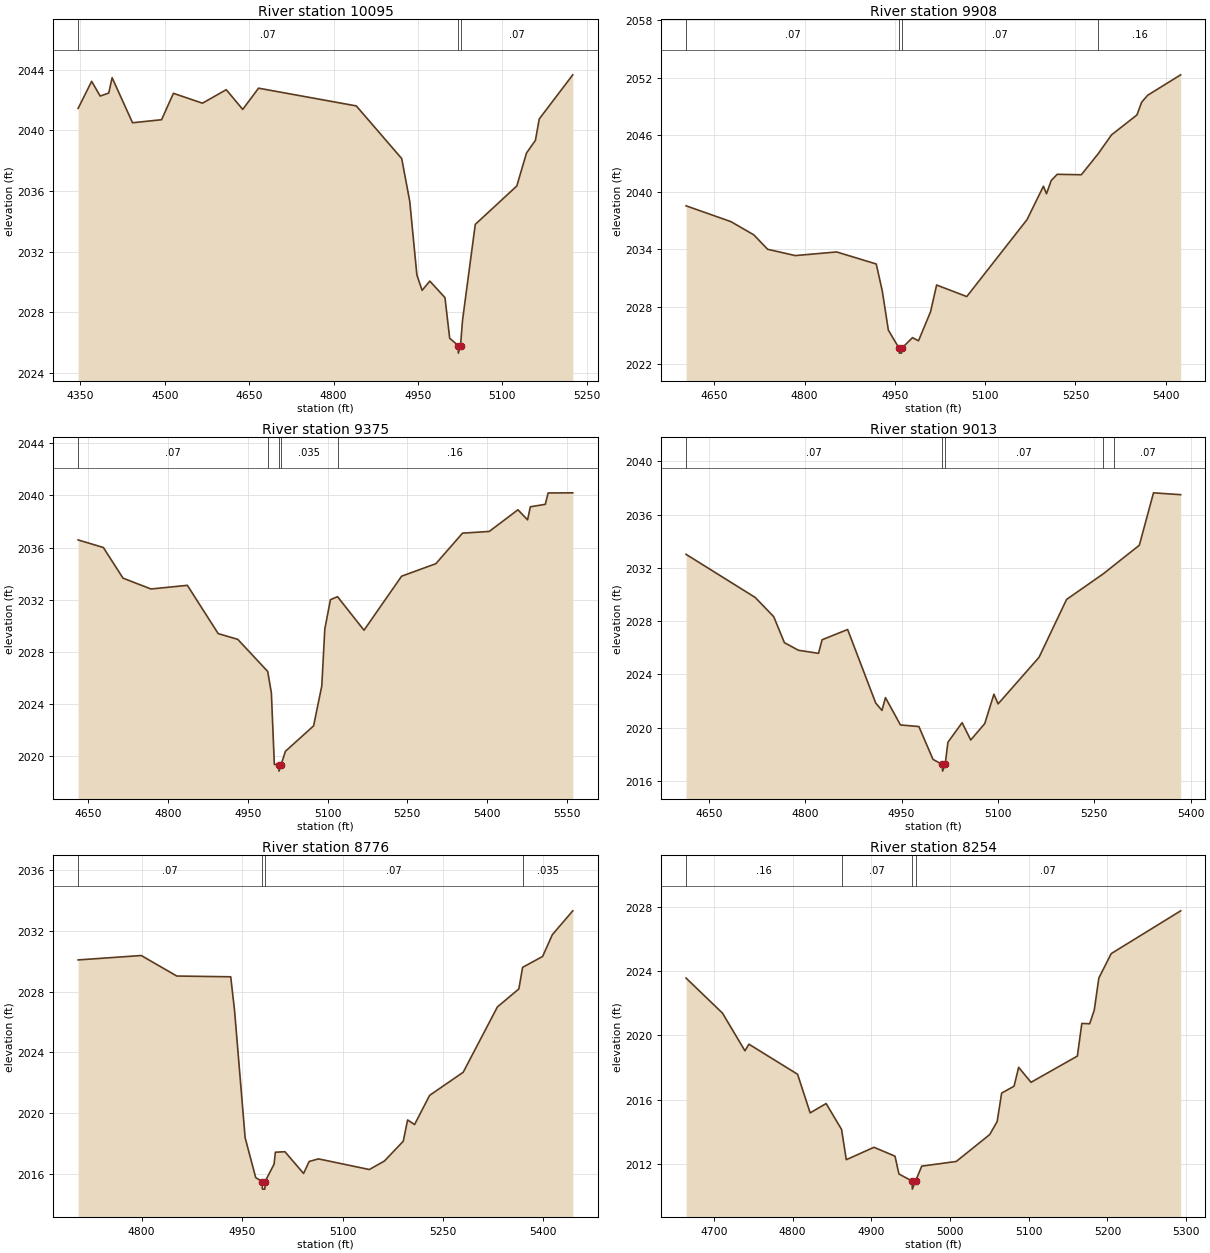
Type RM Length L Ch R = 1,10095,187,187,187
BEGIN DESCRIPTION:
298
END DESCRIPTION:
XS GIS Cut Line= 3
      1541762.28      6780384.31      1541410.31      6779835.32
      1541205.03      6779738.02
#Sta/Elev= 30
  4346.0 2041.44  4370.0 2043.22  4385.2 2042.25  4400.4 2042.45  4406.4 2043.46
  4442.7 2040.49  4494.3 2040.69  4515.4 2042.43  4567.0 2041.78  4609.3 2042.67
  4638.6 2041.37  4666.7 2042.77  4840.5 2041.60  4921.2 2038.13  4935.5 2035.31
  4948.2 2030.45  4957.5 2029.44  4971.2 2030.05  4998.1 2028.96  5006.5 2026.28
  5021.6 2025.80  5021.9 2025.30  5025.8 2025.80  5029.3 2027.46  5052.0 2033.79
  5125.8 2036.32  5143.0 2038.49  5158.9 2039.33  5165.7 2040.74  5225.3 2043.65
#Mann=3,-1,0
  4346.0    0.07       0  5021.6    0.07       0  5025.8    0.07       0
Bank Sta=5021.6,5025.8
Exp/Cntr=0.3,0.1

Type RM Length L Ch R = 1,9908,533,533,533
BEGIN DESCRIPTION:
871
END DESCRIPTION:
XS GIS Cut Line= 3
      1541706.97      6779945.78      1541595.85      6779705.01
      1541040.26      6779667.98
#Sta/Elev= 30
  4602.9 2038.57  4677.6 2036.91  4715.5 2035.53  4738.5 2034.02  4784.4 2033.36
  4853.2 2033.74  4919.0 2032.48  4929.1 2029.62  4939.1 2025.56  4957.0 2023.65
  4957.3 2023.15  4961.0 2023.15  4961.2 2023.65  4979.2 2024.77  4989.2 2024.44
  5009.2 2027.48  5019.3 2030.28  5069.4 2029.07  5169.6 2037.13  5196.8 2040.62
  5201.9 2039.83  5209.7 2041.21  5219.7 2041.87  5259.8 2041.82  5287.8 2044.02
  5309.9 2045.99  5352.2 2048.08  5360.0 2049.41  5370.0 2050.14  5424.9 2052.28
#Mann=4,-1,0
  4602.9    0.07       0  4957.0    0.07       0  4961.2    0.07       0
  5287.8    0.16       0
Bank Sta=4957,4961.2
Exp/Cntr=0.3,0.1

Type RM Length L Ch R = 1,9375,362,362,362
BEGIN DESCRIPTION:
297
END DESCRIPTION:
XS GIS Cut Line= 3
      1541705.01      6779888.04      1541535.67      6779380.94
      1541156.02      6779269.83
#Sta/Elev= 30
  4630.9 2036.59  4678.3 2036.01  4715.3 2033.66  4767.9 2032.83  4836.3 2033.11
  4894.3 2029.41  4931.1 2028.97  4987.4 2026.51  4994.3 2024.86  4999.9 2019.38
  5008.3 2019.37  5008.6 2018.87  5012.6 2019.37  5020.7 2020.39  5073.7 2022.34
  5089.1 2025.40  5094.8 2029.77  5105.4 2032.01  5118.7 2032.24  5168.5 2029.67
  5239.2 2033.81  5303.7 2034.77  5353.8 2037.11  5404.0 2037.24  5458.0 2038.90
  5476.1 2038.13  5481.3 2039.13  5509.5 2039.32  5514.7 2040.19  5561.1 2040.20
#Mann=5,-1,0
  4630.9    0.07       0  4987.4   0.035       0  5008.3   0.035       0
  5012.6   0.035       0  5118.7    0.16       0
Bank Sta=5008.3,5012.6
Exp/Cntr=0.3,0.1

Type RM Length L Ch R = 1,9013,237,237,237
BEGIN DESCRIPTION:
296
END DESCRIPTION:
XS GIS Cut Line= 3
      1542055.01      6779738.01      1541899.10      6779385.44
      1541604.96      6779137.97
#Sta/Elev= 30
  4614.5 2033.02  4722.1 2029.78  4750.9 2028.34  4767.6 2026.38  4789.5 2025.81
  4820.7 2025.58  4826.2 2026.60  4866.0 2027.37  4909.7 2021.85  4919.4 2021.29
  4924.9 2022.25  4948.2 2020.20  4976.9 2020.08  4998.9 2017.61  5013.5 2017.23
  5013.8 2016.73  5017.8 2017.23  5022.1 2018.90  5044.2 2020.37  5057.6 2019.07
  5079.4 2020.30  5093.7 2022.51  5100.2 2021.78  5163.9 2025.28  5206.8 2029.63
  5263.5 2031.54  5281.0 2032.21  5320.0 2033.70  5342.1 2037.64  5384.4 2037.50
#Mann=5,-1,0
  4614.5    0.07       0  5013.5    0.07       0  5017.8    0.07       0
  5263.5    0.16       0  5281.0    0.07       0
Bank Sta=5013.5,5017.8
Exp/Cntr=0.3,0.1

Type RM Length L Ch R = 1,8776,522,522,522
BEGIN DESCRIPTION:
295
END DESCRIPTION:
XS GIS Cut Line= 3
      1542255.01      6779638.01      1542107.98      6779382.61
      1541904.98      6778987.96
#Sta/Elev= 30
  4705.3 2030.08  4799.5 2030.37  4852.6 2029.02  4933.1 2028.97  4938.8 2026.77
  4954.6 2018.39  4970.4 2015.76  4980.1 2015.50  4980.4 2015.00  4984.1 2015.00
  4984.4 2015.50  4997.8 2016.64  4999.8 2017.43  5014.1 2017.46  5041.9 2016.03
  5050.2 2016.82  5064.1 2016.99  5140.1 2016.29  5162.6 2016.85  5190.7 2018.15
  5197.2 2019.55  5207.6 2019.25  5230.1 2021.17  5280.2 2022.69  5331.3 2026.99
  5363.3 2028.17  5368.9 2029.59  5398.8 2030.31  5413.3 2031.74  5443.8 2033.31
#Mann=4,-1,0
  4705.3    0.07       0  4980.1    0.07       0  4984.4    0.07       0
  5368.9   0.035       0
Bank Sta=4980.1,4984.4
Exp/Cntr=0.3,0.1

Type RM Length L Ch R = 1,8254,587,587,587
BEGIN DESCRIPTION:
294
END DESCRIPTION:
XS GIS Cut Line= 3
      1542402.39      6779373.74      1542347.85      6779034.76
      1542204.98      6778787.97
#Sta/Elev= 30
  4664.6 2023.57  4710.9 2021.39  4739.4 2019.05  4744.5 2019.46  4806.3 2017.59
  4822.3 2015.19  4842.6 2015.77  4862.2 2014.16  4868.2 2012.28  4903.4 2013.05
  4930.1 2012.50  4935.1 2011.39  4951.9 2010.95  4952.1 2010.45  4956.2 2010.95
  4964.1 2011.88  5007.9 2012.17  5050.4 2013.84  5059.9 2014.65  5065.6 2016.42
  5081.4 2016.85  5087.2 2018.02  5102.9 2017.09  5161.8 2018.72  5167.5 2020.75
  5177.5 2020.73  5183.3 2021.58  5189.1 2023.57  5204.8 2025.09  5293.1 2027.75
#Mann=4,-1,0
  4664.6    0.16       0  4862.2    0.07       0  4951.9    0.07       0
  4956.2    0.07       0
Bank Sta=4951.9,4956.2
Exp/Cntr=0.3,0.1

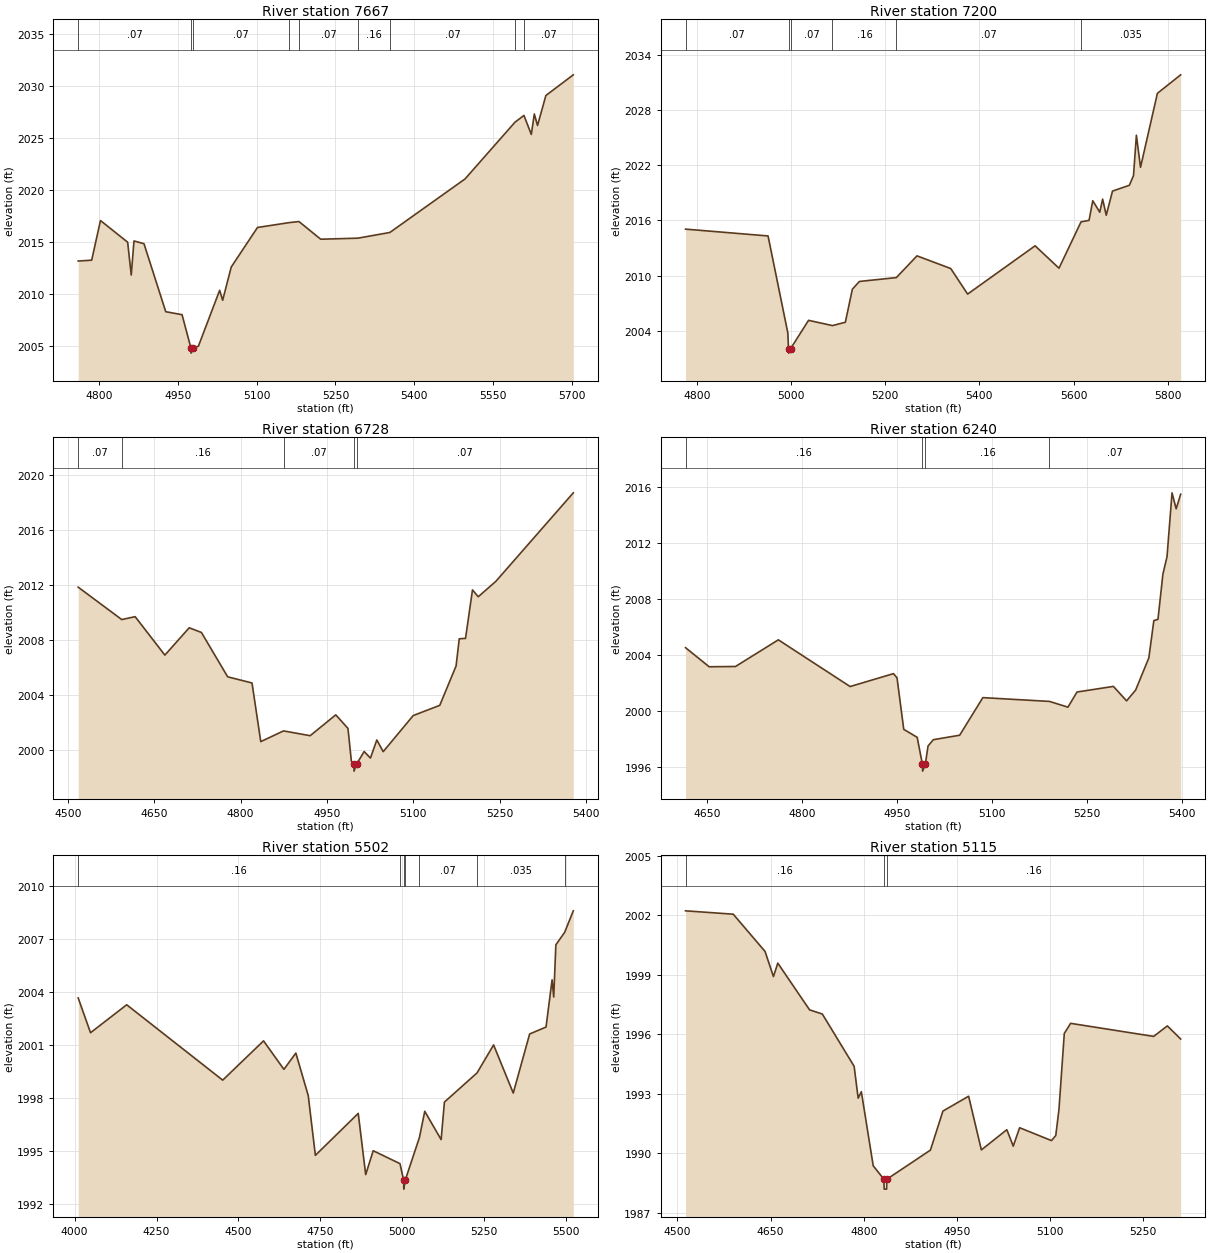
Type RM Length L Ch R = 1,7667,467,467,467
BEGIN DESCRIPTION:
293
END DESCRIPTION:
XS GIS Cut Line= 3
      1542623.75      6779338.97      1542684.93      6779107.83
      1542354.99      6778487.97
#Sta/Elev= 30
  4760.9 2013.14  4786.6 2013.22  4803.3 2017.04  4855.0 2014.95  4861.8 2011.79
  4867.0 2015.07  4886.0 2014.81  4927.4 2008.26  4958.4 2007.97  4975.2 2004.77
  4975.5 2004.27  4979.6 2004.77  4989.5 2004.94  5029.9 2010.32  5035.6 2009.36
  5051.9 2012.56  5101.8 2016.37  5162.4 2016.84  5180.7 2016.94  5222.0 2015.24
  5292.7 2015.34  5353.5 2015.89  5496.3 2021.04  5591.4 2026.51  5608.4 2027.16
  5622.4 2025.33  5628.1 2027.30  5634.2 2026.19  5650.1 2029.08  5702.2 2031.07
#Mann=9,-1,0
  4760.9    0.07       0  4975.2    0.07       0  4979.6    0.07       0
  5162.4    0.16       0  5180.7    0.07       0  5292.7    0.16       0
  5353.5    0.07       0  5591.4   0.035       0  5608.4    0.07       0
Bank Sta=4975.2,4979.6
Exp/Cntr=0.3,0.1

Type RM Length L Ch R = 1,7200,472,472,472
BEGIN DESCRIPTION:
292
END DESCRIPTION:
XS GIS Cut Line= 3
      1543214.00      6779091.59      1543085.73      6778908.08
      1542404.97      6778437.98
#Sta/Elev= 30
  4776.1 2015.05  4951.3 2014.31  4993.3 2003.78  4994.7 2002.09  4995.0 2001.59
  4999.3 2002.09  5037.3 2005.15  5087.9 2004.58  5115.4 2004.94  5130.3 2008.53
  5145.2 2009.37  5223.7 2009.79  5267.5 2012.15  5339.2 2010.77  5375.0 2008.00
  5518.3 2013.24  5569.0 2010.81  5615.8 2015.84  5632.8 2016.00  5640.7 2018.13
  5655.6 2016.89  5661.6 2018.31  5669.3 2016.56  5682.6 2019.18  5718.4 2019.81
  5727.2 2020.86  5733.3 2025.24  5742.1 2021.76  5777.9 2029.79  5827.3 2031.80
#Mann=6,-1,0
  4776.1    0.07       0  4994.7    0.07       0  4999.3    0.07       0
  5087.9    0.16       0  5223.7    0.07       0  5615.8   0.035       0
Bank Sta=4994.7,4999.3
Exp/Cntr=0.3,0.1

Type RM Length L Ch R = 1,6728,488,488,488
BEGIN DESCRIPTION:
291
END DESCRIPTION:
XS GIS Cut Line= 3
      1543322.53      6778887.63      1543062.86      6778481.20
      1542904.99      6778137.97
#Sta/Elev= 30
  4517.7 2011.86  4593.4 2009.50  4616.7 2009.71  4668.3 2006.91  4710.6 2008.90
  4731.8 2008.56  4777.4 2005.33  4819.7 2004.88  4834.9 2000.61  4874.5 2001.39
  4920.7 2001.04  4965.2 2002.56  4986.4 2001.57  4992.3 1999.18  4996.6 1998.96
  4997.0 1998.46  5001.2 1998.96  5014.5 1999.89  5025.4 1999.41  5036.5 2000.73
  5047.6 1999.88  5099.8 2002.51  5145.8 2003.25  5174.2 2006.12  5179.7 2008.10
  5190.6 2008.13  5202.7 2011.66  5212.7 2011.16  5243.2 2012.28  5377.8 2018.73
#Mann=5,-1,0
  4517.7    0.07       0  4593.4    0.16       0  4874.5    0.07       0
  4996.6    0.07       0  5001.2    0.07       0
Bank Sta=4996.6,5001.2
Exp/Cntr=0.3,0.1

Type RM Length L Ch R = 1,6240,738,738,738
BEGIN DESCRIPTION:
290
END DESCRIPTION:
XS GIS Cut Line= 3
      1543587.28      6778653.24      1543461.63      6778290.70
      1543155.03      6778038.02
#Sta/Elev= 30
  4616.3 2004.52  4653.6 2003.16  4695.1 2003.18  4762.7 2005.08  4875.9 2001.75
  4944.3 2002.67  4949.9 2002.37  4960.5 1998.70  4981.7 1998.13  4989.9 1996.22
  4990.3 1995.72  4994.6 1996.22  4998.8 1997.51  5007.1 1997.96  5048.7 1998.28
  5085.3 2000.96  5190.4 2000.69  5219.5 2000.28  5233.8 2001.36  5291.2 2001.76
  5312.0 2000.73  5326.3 2001.50  5347.1 2003.79  5355.0 2006.45  5361.5 2006.54
  5369.3 2009.76  5375.8 2011.01  5383.7 2015.56  5390.2 2014.42  5397.3 2015.46
#Mann=4,-1,0
  4616.3    0.16       0  4989.9    0.07       0  4994.6    0.16       0
  5190.4    0.07       0
Bank Sta=4989.9,4994.6
Exp/Cntr=0.3,0.1

Type RM Length L Ch R = 1,5502,387,387,387
BEGIN DESCRIPTION:
870
END DESCRIPTION:
XS GIS Cut Line= 5
      1543600.48      6778635.60      1543577.33      6778357.79
      1543697.70      6778010.57      1543521.78      6777691.13
      1543021.82      6777681.87
#Sta/Elev= 30
  4010.9 2003.65  4048.6 2001.68  4159.0 2003.26  4452.0 1999.00  4576.6 2001.22
  4638.8 1999.61  4675.2 2000.53  4713.0 1998.13  4734.8 1994.75  4865.6 1997.12
  4888.4 1993.66  4911.3 1995.01  4993.0 1994.28  5004.2 1993.34  5004.6 1992.84
  5008.9 1993.34  5052.2 1995.75  5068.6 1997.24  5118.6 1995.64  5128.6 1997.76
  5228.2 1999.41  5278.7 2000.99  5338.7 1998.27  5388.7 2001.61  5438.7 2002.00
  5457.2 2004.67  5462.2 2003.70  5468.7 2006.65  5495.4 2007.35  5521.9 2008.57
#Mann=7,-1,0
  4010.9    0.16       0  4993.0    0.07       0  5004.2    0.07       0
  5008.9    0.07       0  5052.2    0.07       0  5228.2   0.035       0
  5495.4    0.07       0
Bank Sta=5004.2,5008.9
Exp/Cntr=0.3,0.1

Type RM Length L Ch R = 1,5115,507,507,507
BEGIN DESCRIPTION:
289
END DESCRIPTION:
XS GIS Cut Line= 3
      1543980.01      6778263.04      1543875.42      6777787.50
      1543804.28      6777485.67
#Sta/Elev= 30
  4513.1 2002.23  4589.9 2002.06  4641.1 2000.18  4654.6 1998.91  4661.6 1999.59
  4712.8 1997.23  4733.3 1997.02  4784.5 1994.38  4791.0 1992.77  4796.1 1993.10
  4815.2 1989.36  4832.4 1988.68  4832.8 1988.18  4836.8 1988.18  4837.1 1988.68
  4907.3 1990.15  4927.4 1992.12  4968.8 1992.87  4989.3 1990.16  5030.3 1991.18
  5040.6 1990.35  5050.9 1991.28  5102.2 1990.63  5109.1 1990.89  5114.2 1992.20
  5122.8 1996.04  5133.0 1996.55  5266.6 1995.89  5288.7 1996.42  5310.1 1995.76
#Mann=3,-1,0
  4513.1    0.16       0  4832.4    0.07       0  4837.1    0.16       0
Bank Sta=4832.4,4837.1
Exp/Cntr=0.3,0.1

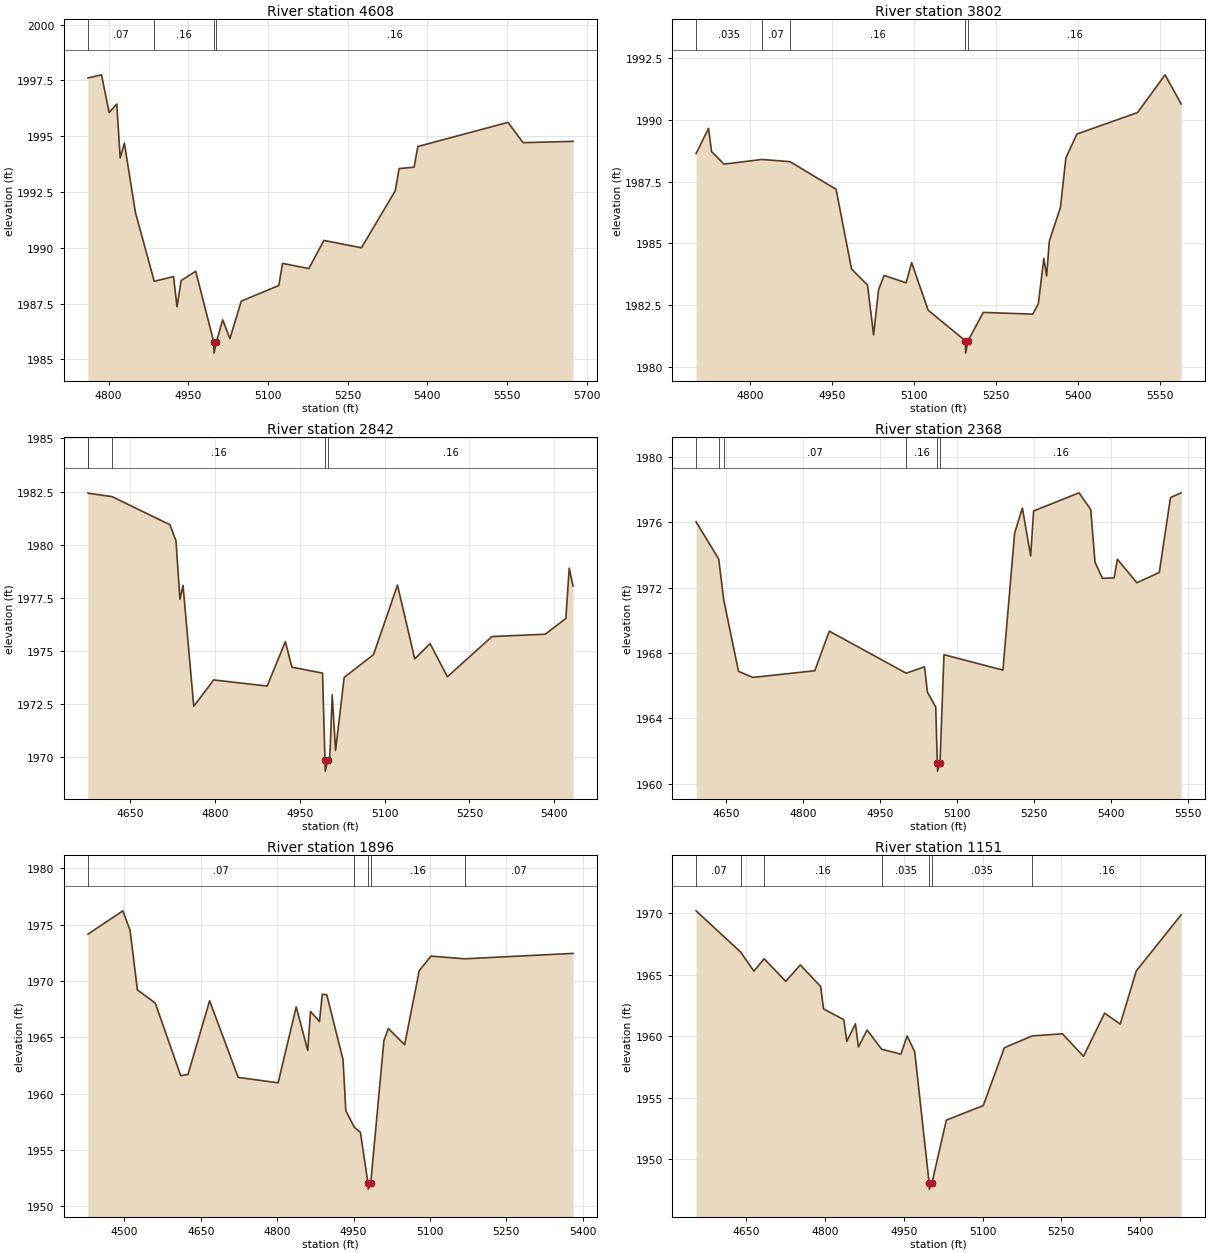
Type RM Length L Ch R = 1,4608,806,806,806
BEGIN DESCRIPTION:
822
END DESCRIPTION:
XS GIS Cut Line= 3
      1544424.98      6778054.31      1544260.02      6777854.63
      1543795.62      6777394.57
#Sta/Elev= 30
  4761.2 1997.61  4786.8 1997.75  4801.1 1996.06  4815.5 1996.44  4821.9 1994.03
  4829.8 1994.69  4850.6 1991.58  4886.0 1988.50  4922.3 1988.71  4928.8 1987.36
  4936.6 1988.53  4964.0 1988.95  4998.0 1985.78  4998.4 1985.28  5002.9 1985.78
  5014.8 1986.77  5028.4 1985.93  5049.7 1987.61  5120.4 1988.31  5127.4 1989.30
  5176.9 1989.07  5205.2 1990.33  5275.9 1990.00  5339.6 1992.56  5346.7 1993.55
  5374.9 1993.61  5382.0 1994.54  5551.7 1995.62  5580.0 1994.71  5673.9 1994.77
#Mann=4,-1,0
  4761.2    0.07       0  4886.0    0.16       0  4998.0    0.07       0
  5002.9    0.16       0
Bank Sta=4998,5002.9
Exp/Cntr=0.3,0.1

Type RM Length L Ch R = 1,3802,960,960,960
BEGIN DESCRIPTION:
288
END DESCRIPTION:
XS GIS Cut Line= 3
      1544780.02      6777413.01      1544510.31      6777285.81
      1543925.82      6777212.27
#Sta/Elev= 30
  4701.8 1988.64  4724.6 1989.66  4730.1 1988.72  4752.9 1988.21  4822.3 1988.40
  4873.6 1988.31  4957.9 1987.19  4986.2 1983.96  5015.4 1983.31  5026.5 1981.29
  5035.6 1983.12  5045.7 1983.70  5086.0 1983.40  5096.1 1984.22  5126.3 1982.29
  5194.4 1981.05  5194.8 1980.55  5199.3 1981.05  5227.1 1982.20  5317.8 1982.13
  5327.9 1982.56  5337.9 1984.39  5343.0 1983.68  5348.0 1985.10  5368.2 1986.45
  5378.3 1988.47  5398.4 1989.43  5509.3 1990.30  5559.7 1991.83  5589.1 1990.65
#Mann=5,-1,0
  4701.8   0.035       0  4822.3    0.07       0  4873.6    0.16       0
  5194.4    0.07       0  5199.3    0.16       0
Bank Sta=5194.4,5199.3
Exp/Cntr=0.3,0.1

Type RM Length L Ch R = 1,2842,474,474,474
BEGIN DESCRIPTION:
287
END DESCRIPTION:
XS GIS Cut Line= 3
      1545029.99      6777012.97      1544875.00      6776617.77
      1544508.70      6776386.69
#Sta/Elev= 30
  4575.5 1982.44  4576.1 1982.42  4618.3 1982.26  4720.5 1980.94  4731.2 1980.18
  4738.2 1977.43  4743.6 1978.09  4762.6 1972.40  4797.8 1973.64  4892.3 1973.35
  4924.6 1975.44  4936.1 1974.24  4990.3 1973.96  4994.6 1969.85  4995.0 1969.35
  4999.8 1969.85  5003.0 1969.85  5007.4 1972.94  5013.3 1970.32  5028.6 1973.76
  5080.4 1974.83  5122.8 1978.10  5153.3 1974.63  5180.4 1975.35  5211.0 1973.79
  5289.9 1975.68  5384.0 1975.79  5420.5 1976.53  5426.4 1978.90  5433.1 1978.06
#Mann=5,-1,0
  4575.5    0.07       0  4576.1   0.035       0  4618.3    0.16       0
  4994.6    0.07       0  4999.8    0.16       0
Bank Sta=4994.6,4999.8
Exp/Cntr=0.3,0.1

Type RM Length L Ch R = 1,2368,472,472,472
BEGIN DESCRIPTION:
286
END DESCRIPTION:
XS GIS Cut Line= 3
      1545430.00      6776762.99      1545241.37      6776401.21
      1544770.47      6776143.72
#Sta/Elev= 30
  4592.0 1976.03  4636.1 1973.75  4646.0 1971.22  4674.7 1966.88  4702.5 1966.51
  4823.2 1966.92  4851.5 1969.34  5001.2 1966.77  5036.9 1967.16  5042.6 1965.61
  5058.7 1964.70  5061.8 1961.28  5062.2 1960.78  5067.0 1961.28  5074.8 1967.90
  5189.6 1966.96  5212.4 1975.34  5227.5 1976.87  5243.6 1973.94  5249.3 1976.69
  5337.8 1977.80  5360.6 1976.78  5368.9 1973.56  5383.4 1972.57  5406.2 1972.60
  5412.5 1973.74  5450.4 1972.30  5494.1 1972.93  5515.9 1977.51  5536.7 1977.80
#Mann=6,-1,0
  4592.0    0.07       0  4636.1   0.035       0  4646.0    0.07       0
  5001.2    0.16       0  5061.8    0.07       0  5067.0    0.16       0
Bank Sta=5061.8,5067
Exp/Cntr=0.3,0.1

Type RM Length L Ch R = 1,1896,745,745,745
BEGIN DESCRIPTION:
821
END DESCRIPTION:
XS GIS Cut Line= 3
      1545861.58      6776328.59      1545559.50      6776052.55
      1545064.73      6775828.60
#Sta/Elev= 30
  4428.6 1974.17  4497.3 1976.24  4511.5 1974.47  4525.7 1969.22  4560.8 1968.05
  4610.8 1961.60  4625.0 1961.71  4667.5 1968.26  4723.6 1961.45  4802.0 1960.97
  4837.5 1967.71  4860.1 1963.85  4865.6 1967.31  4883.2 1966.41  4888.7 1968.83
  4897.6 1968.78  4929.4 1963.04  4934.9 1958.49  4951.5 1957.03  4963.5 1956.58
  4978.5 1952.03  4978.9 1951.53  4983.7 1952.03  5009.7 1964.72  5018.4 1965.79
  5050.4 1964.35  5079.0 1970.92  5102.1 1972.22  5168.2 1971.98  5380.9 1972.46
#Mann=5,-1,0
  4428.6    0.07       0  4951.5    0.16       0  4978.5    0.07       0
  4983.7    0.16       0  5168.2    0.07       0
Bank Sta=4978.5,4983.7
Exp/Cntr=0.3,0.1

Type RM Length L Ch R = 1,1151,614,614,614
BEGIN DESCRIPTION:
820
END DESCRIPTION:
XS GIS Cut Line= 3
      1546090.75      6775940.56      1545911.06      6775594.22
      1545379.89      6775542.14
#Sta/Elev= 30
  4554.3 1970.18  4639.1 1966.83  4664.4 1965.28  4684.0 1966.28  4725.1 1964.45
  4752.8 1965.78  4791.5 1964.03  4797.1 1962.20  4835.7 1961.33  4841.3 1959.56
  4857.8 1960.99  4863.5 1959.11  4880.0 1960.49  4907.9 1958.92  4944.5 1958.53
  4956.3 1960.01  4970.7 1958.71  4998.2 1948.05  4998.6 1947.55  5003.5 1948.05
  5031.0 1953.16  5101.3 1954.35  5141.5 1959.05  5194.5 1960.01  5252.0 1960.18
  5292.2 1958.35  5332.4 1961.86  5362.2 1960.97  5392.7 1965.29  5478.2 1969.86
#Mann=7,-1,0
  4554.3    0.07       0  4639.1   0.035       0  4684.0    0.16       0
  4907.9   0.035       0  4998.2   0.035       0  5003.5   0.035       0
  5194.5    0.16       0
Bank Sta=4998.2,5003.5
Exp/Cntr=0.3,0.1

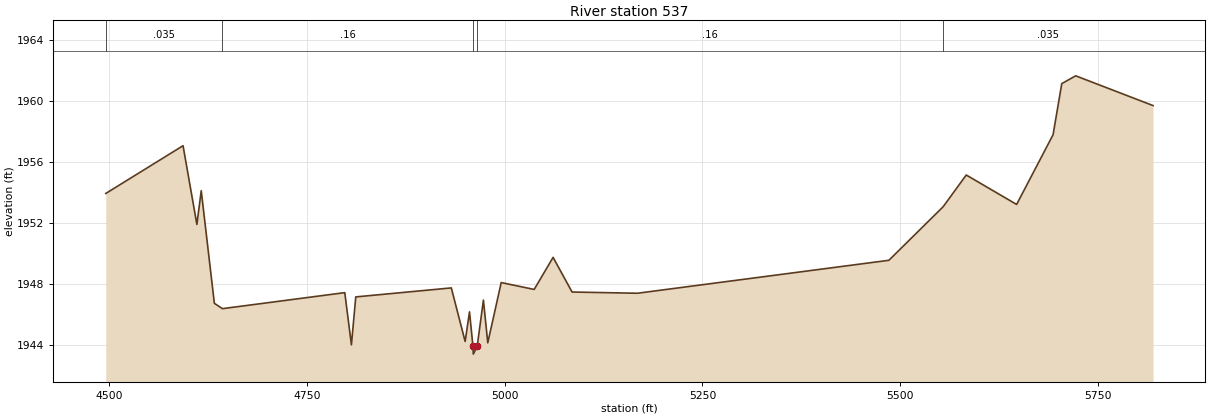
Type RM Length L Ch R = 1,537,0,0,0
BEGIN DESCRIPTION:
285
END DESCRIPTION:
XS GIS Cut Line= 4
      1546479.99      6775762.98      1546264.08      6775288.98
      1546080.00      6775213.00      1545529.96      6775463.02
#Sta/Elev= 30
  4495.6 1953.95  4593.3 1957.08  4610.8 1951.92  4616.3 1954.13  4632.9 1946.75
  4643.1 1946.40  4797.8 1947.45  4806.2 1944.03  4811.7 1947.17  4932.5 1947.76
  4950.0 1944.25  4955.5 1946.19  4959.9 1943.92  4960.3 1943.42  4965.2 1943.92
  4973.1 1946.96  4978.6 1944.16  4995.6 1948.11  5037.3 1947.66  5061.2 1949.76
  5085.2 1947.49  5167.8 1947.41  5485.8 1949.57  5554.4 1953.08  5583.6 1955.16
  5647.3 1953.23  5693.4 1957.80  5704.4 1961.15  5722.0 1961.66  5819.8 1959.71
#Mann=5,-1,0
  4495.6   0.035       0  4643.1    0.16       0  4959.9    0.07       0
  4965.2    0.16       0  5554.4   0.035       0
Bank Sta=4959.9,4965.2
Exp/Cntr=0.3,0.1

Chan Stop Cuts=-1