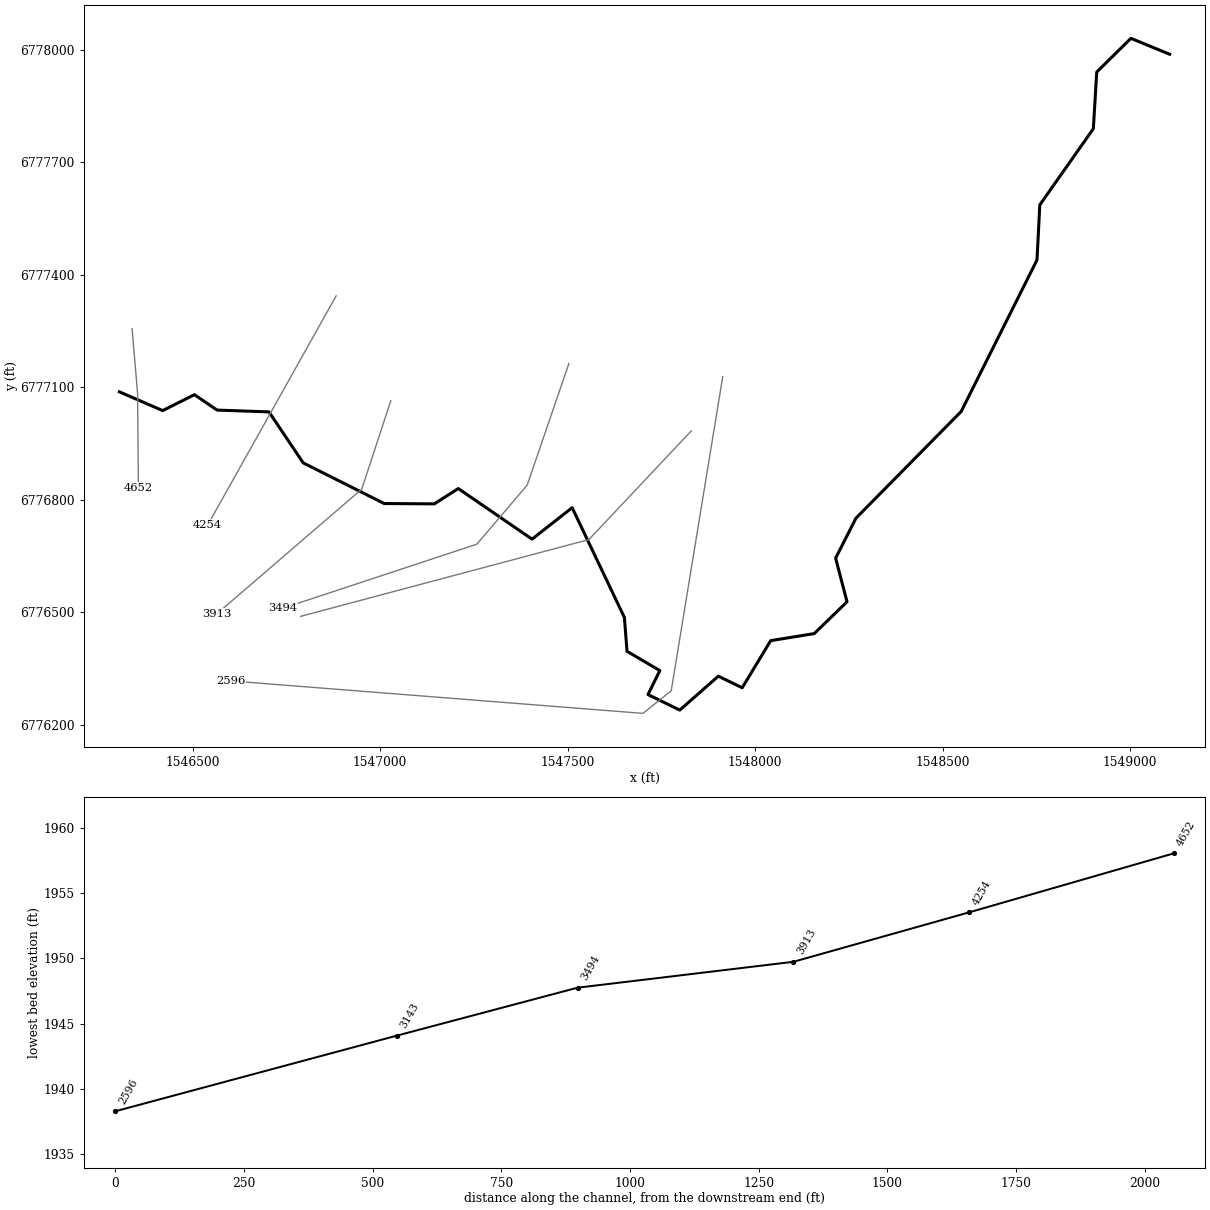
--- Elm 97.prj (project) ---

Proj Title=Elm 97 Base Level Engineering
Current Plan=p01
Default Exp/Contr=0.3,0.1
English Units
Geom File=g01
Flow File=f01
Plan File=p01
BEGIN DESCRIPTION:
Elm 97
END DESCRIPTION:

--- Elm 97.p01 (plan) ---

Plan Title=Multiple Run
Short Identifier=Multiple
Geom File=g01
Flow File=f01
Subcritical Flow
K Sum by GR= 0
Std Step Tol= 0.01
Critical Tol= 0.01
Num of Std Step Trials= 20
Max Error Tol= 0.3
Flow Tol Ratio= 0.001
Split Flow NTrial= 30
Split Flow Tol= 0.02
Split Flow Ratio= 0.02
Log Output Level= 0
Friction Slope Method= 1
Unsteady Friction Slope Method= 2
Unsteady Bridges Friction Slope Method= 1
Parabolic Critical Depth
Global Vel Dist=  1 , 1 , 1
Global Log Level= 0
CheckData=True
Encroach Param= -1, 0, 0, 0
BEGIN DESCRIPTION:
Multiple Run
END DESCRIPTION:

--- Elm 97.f01 (steady flow) ---

Flow Title=Multiple
Number of Profiles=7
Profile Names=10-year,25-year,50-year,1pct_min,100-year,1pct_plu,500-year
River Rch & RM= Elm 97,Reach-1,4652
     107     141     166     123     197     271     277
Boundary for River Rch & Prof#=Elm 97,Reach-1,1
Up Type=0
Dn Type=3
Dn Slope=0.005
Boundary for River Rch & Prof#=Elm 97,Reach-1,2
Up Type=0
Dn Type=3
Dn Slope=0.005
Boundary for River Rch & Prof#=Elm 97,Reach-1,3
Up Type=0
Dn Type=3
Dn Slope=0.005
Boundary for River Rch & Prof#=Elm 97,Reach-1,4
Up Type=0
Dn Type=3
Dn Slope=0.005
Boundary for River Rch & Prof#=Elm 97,Reach-1,5
Up Type=0
Dn Type=3
Dn Slope=0.005
Boundary for River Rch & Prof#=Elm 97,Reach-1,6
Up Type=0
Dn Type=3
Dn Slope=0.005
Boundary for River Rch & Prof#=Elm 97,Reach-1,7
Up Type=0
Dn Type=3
Dn Slope=0.005

--- Elm 97.g01 (geometry) ---

Geom Title=Existing Conditions

River Reach=Elm 97,Reach-1
Reach XY= 30
      1546305.00      6777088.00      1546420.41      6777038.04
      1546504.99      6777080.41      1546565.44      6777039.39
      1546703.75      6777034.54      1546795.00      6776898.63
      1547010.93      6776790.23      1547144.56      6776789.38
      1547208.41      6776830.19      1547405.09      6776695.31
      1547512.00      6776779.17      1547651.34      6776486.43
      1547658.22      6776396.34      1547745.76      6776344.92
      1547714.19      6776280.96      1547798.87      6776239.60
      1547901.68      6776329.98      1547965.32      6776299.11
      1548041.35      6776424.74      1548157.44      6776443.52
      1548244.81      6776528.30      1548214.43      6776644.61
      1548268.61      6776751.21      1548549.17      6777035.70
      1548751.24      6777439.56      1548758.76      6777586.44
      1548901.45      6777789.47      1548910.47      6777940.48
      1549001.59      6778030.42      1549105.00      6777988.00

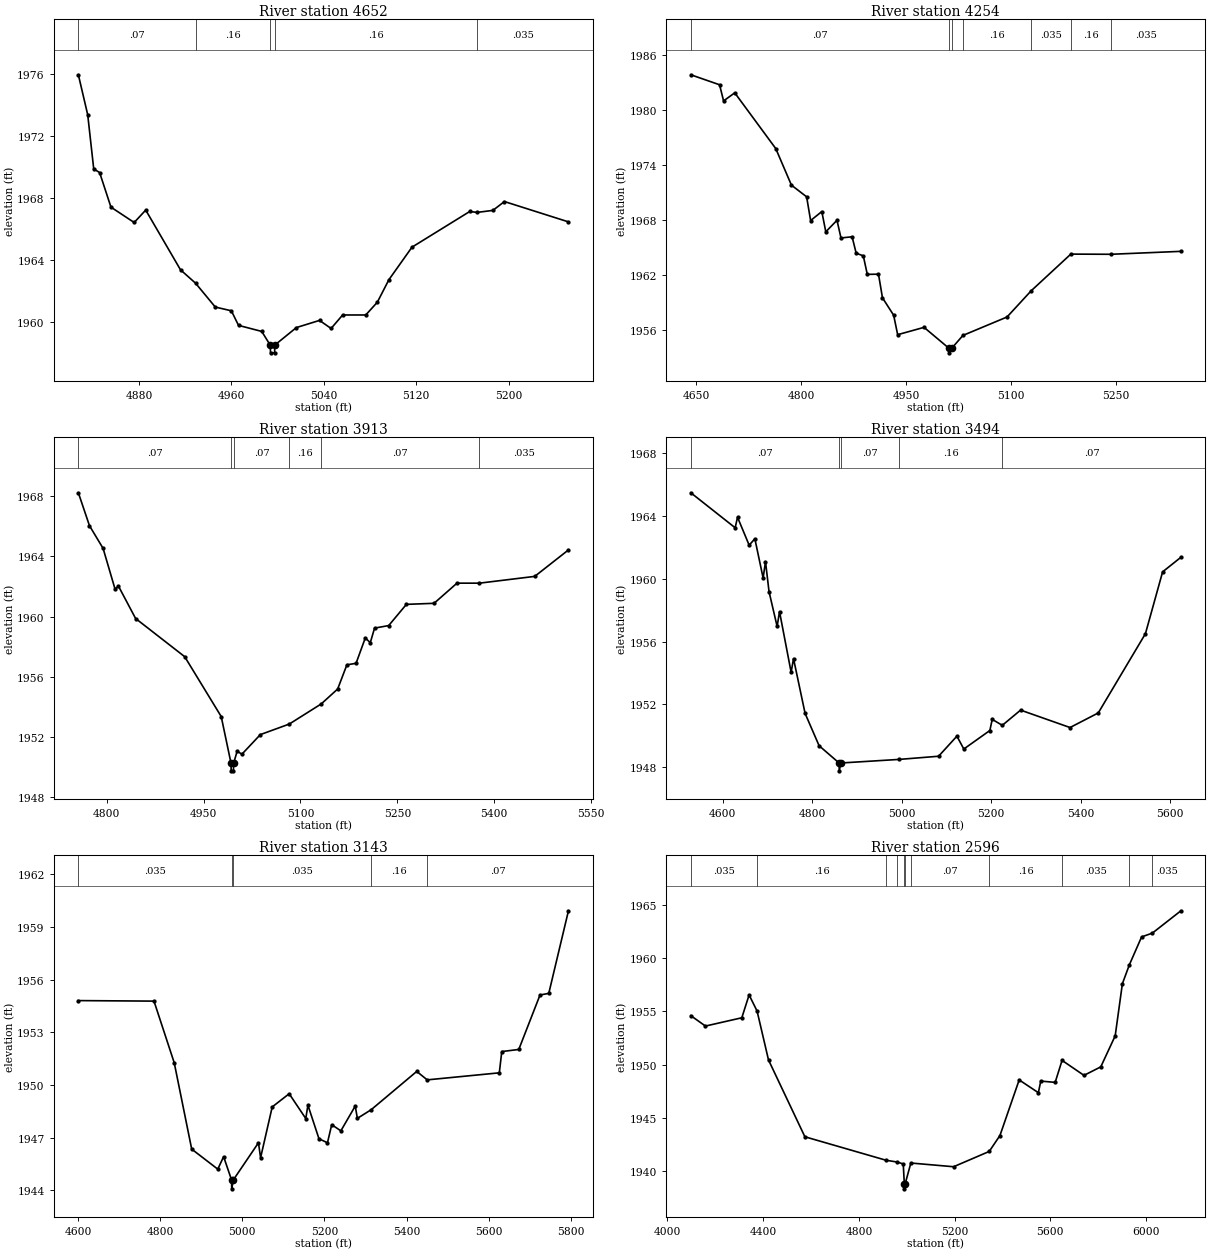
Type RM Length L Ch R = 1,4652,398,398,398
BEGIN DESCRIPTION:
459
END DESCRIPTION:
XS GIS Cut Line= 3
      1546338.85      6777256.08      1546353.51      6777084.31
      1546355.66      6776832.62
#Sta/Elev= 30
  4827.6 1975.96  4835.7 1973.38  4840.9 1969.89  4846.0 1969.66  4855.8 1967.43
  4875.9 1966.44  4885.9 1967.24  4916.0 1963.39  4929.0 1962.53  4946.1 1960.99
  4960.0 1960.75  4966.2 1959.81  4986.3 1959.42  4993.6 1958.54  4993.9 1958.04
  4997.4 1958.04  4997.6 1958.54  5016.3 1959.67  5036.3 1960.13  5046.3 1959.61
  5056.3 1960.48  5076.3 1960.48  5086.3 1961.30  5096.3 1962.75  5116.3 1964.85
  5166.3 1967.15  5172.6 1967.09  5186.3 1967.22  5196.3 1967.79  5251.7 1966.48
#Mann=5,-1,0
  4827.6    0.07       0  4929.0    0.16       0  4993.6    0.07       0
  4997.6    0.16       0  5172.6   0.035       0
Bank Sta=4993.6,4997.6
Exp/Cntr=0.3,0.1

Type RM Length L Ch R = 1,4254,341,341,341
BEGIN DESCRIPTION:
874
END DESCRIPTION:
XS GIS Cut Line= 2
      1546882.87      6777343.87      1546540.37      6776732.92
#Sta/Elev= 30
  4642.1 1983.85  4683.2 1982.76  4688.9 1981.00  4704.9 1981.88  4763.5 1975.80
  4785.9 1971.81  4807.6 1970.54  4813.3 1967.95  4829.3 1968.93  4835.0 1966.72
  4851.0 1967.98  4856.7 1966.05  4872.6 1966.18  4878.4 1964.39  4888.6 1964.10
  4894.3 1962.08  4910.3 1962.10  4916.0 1959.52  4932.0 1957.62  4937.7 1955.50
  4975.4 1956.30  5011.0 1954.02  5011.3 1953.52  5015.0 1954.02  5031.0 1955.42
  5094.0 1957.43  5128.4 1960.28  5185.2 1964.29  5242.5 1964.27  5342.5 1964.59
#Mann=7,-1,0
  4642.1    0.07       0  5011.0    0.07       0  5015.0    0.07       0
  5031.0    0.16       0  5128.4   0.035       0  5185.2    0.16       0
  5242.5   0.035       0
Bank Sta=5011,5015
Exp/Cntr=0.3,0.1

Type RM Length L Ch R = 1,3913,419,419,419
BEGIN DESCRIPTION:
826
END DESCRIPTION:
XS GIS Cut Line= 3
      1547028.58      6777064.35      1546951.20      6776828.83
      1546564.24      6776495.71
#Sta/Elev= 30
  4756.3 1968.23  4773.5 1966.04  4794.6 1964.53  4813.1 1961.82  4818.4 1962.02
  4844.9 1959.87  4920.9 1957.33  4977.4 1953.35  4992.6 1950.24  4992.8 1949.74
  4996.3 1949.74  4996.6 1950.24  5002.0 1951.04  5009.5 1950.85  5038.0 1952.15
  5082.7 1952.85  5132.2 1954.19  5157.6 1955.18  5171.9 1956.79  5186.1 1956.89
  5200.4 1958.58  5208.1 1958.26  5214.7 1959.23  5236.6 1959.40  5264.0 1960.81
  5306.8 1960.88  5342.3 1962.22  5377.0 1962.22  5462.6 1962.67  5514.8 1964.43
#Mann=6,-1,0
  4756.3    0.07       0  4992.6    0.07       0  4996.6    0.07       0
  5082.7    0.16       0  5132.2    0.07       0  5377.0   0.035       0
Bank Sta=4992.6,4996.6
Exp/Cntr=0.3,0.1

Type RM Length L Ch R = 1,3494,351,351,351
BEGIN DESCRIPTION:
873
END DESCRIPTION:
XS GIS Cut Line= 4
      1547503.27      6777163.39      1547392.15      6776839.27
      1547257.89      6776681.87      1546739.66      6776510.67
#Sta/Elev= 30
  4528.9 1965.48  4628.0 1963.25  4633.3 1963.92  4659.3 1962.14  4672.0 1962.55
  4690.5 1960.05  4695.8 1961.09  4703.7 1959.18  4721.8 1956.96  4727.1 1957.91
  4753.1 1954.04  4758.4 1954.91  4784.3 1951.42  4815.6 1949.36  4860.3 1948.26
  4860.6 1947.76  4864.3 1948.26  4995.2 1948.49  5082.6 1948.69  5123.6 1949.97
  5139.0 1949.15  5197.2 1950.33  5202.5 1951.04  5225.0 1950.66  5265.9 1951.63
  5376.4 1950.52  5439.5 1951.45  5544.9 1956.50  5583.3 1960.44  5624.2 1961.37
#Mann=5,-1,0
  4528.9    0.07       0  4860.3    0.07       0  4864.3    0.07       0
  4995.2    0.16       0  5225.0    0.07       0
Bank Sta=4860.3,4864.3
Exp/Cntr=0.3,0.1

Type RM Length L Ch R = 1,3143,547,547,547
BEGIN DESCRIPTION:
825
END DESCRIPTION:
XS GIS Cut Line= 3
      1547829.37      6776983.63      1547556.82      6776694.25
      1546788.15      6776489.50
#Sta/Elev= 30
  4600.9 1954.80  4785.0 1954.77  4834.3 1951.26  4876.8 1946.35  4940.3 1945.21
  4954.5 1945.92  4973.9 1944.59  4974.2 1944.09  4977.9 1944.59  5039.3 1946.71
  5044.5 1945.86  5072.8 1948.75  5114.1 1949.50  5154.5 1948.09  5159.7 1948.85
  5186.6 1946.94  5207.3 1946.71  5217.6 1947.74  5239.9 1947.39  5274.9 1948.80
  5280.1 1948.10  5313.6 1948.59  5424.6 1950.77  5450.1 1950.29  5625.6 1950.69
  5631.6 1951.90  5673.0 1952.02  5724.7 1955.12  5746.0 1955.21  5793.9 1959.91
#Mann=5,-1,0
  4600.9   0.035       0  4973.9   0.035       0  4977.9   0.035       0
  5313.6    0.16       0  5450.1    0.07       0
Bank Sta=4973.9,4977.9
Exp/Cntr=0.3,0.1

Type RM Length L Ch R = 1,2596,0,0,0
BEGIN DESCRIPTION:
824
END DESCRIPTION:
XS GIS Cut Line= 4
      1547913.46      6777128.28      1547776.16      6776291.14
      1547700.78      6776230.83      1546601.25      6776317.42
#Sta/Elev= 30
  4097.7 1954.60  4158.8 1953.62  4310.8 1954.40  4341.2 1956.55  4374.6 1955.03
  4422.3 1950.43  4574.3 1943.20  4913.6 1940.99  4960.6 1940.82  4985.3 1940.64
  4989.7 1938.80  4990.0 1938.30  4993.7 1938.80  5017.1 1940.73  5195.7 1940.38
  5344.6 1941.82  5389.4 1943.32  5469.7 1948.55  5549.9 1947.35  5559.9 1948.44
  5620.1 1948.32  5648.9 1950.39  5740.5 1948.98  5810.7 1949.78  5870.9 1952.70
  5901.0 1957.61  5930.4 1959.40  5981.2 1962.01  6026.3 1962.37  6145.5 1964.47
#Mann=11,-1,0
  4097.7   0.035       0  4374.6    0.16       0  4913.6    0.07       0
  4960.6    0.16       0  4989.7    0.07       0  4993.7    0.16       0
  5017.1    0.07       0  5344.6    0.16       0  5648.9   0.035       0
  5930.4    0.07       0  6026.3   0.035       0
Bank Sta=4989.7,4993.7
Exp/Cntr=0.3,0.1

Chan Stop Cuts=-1