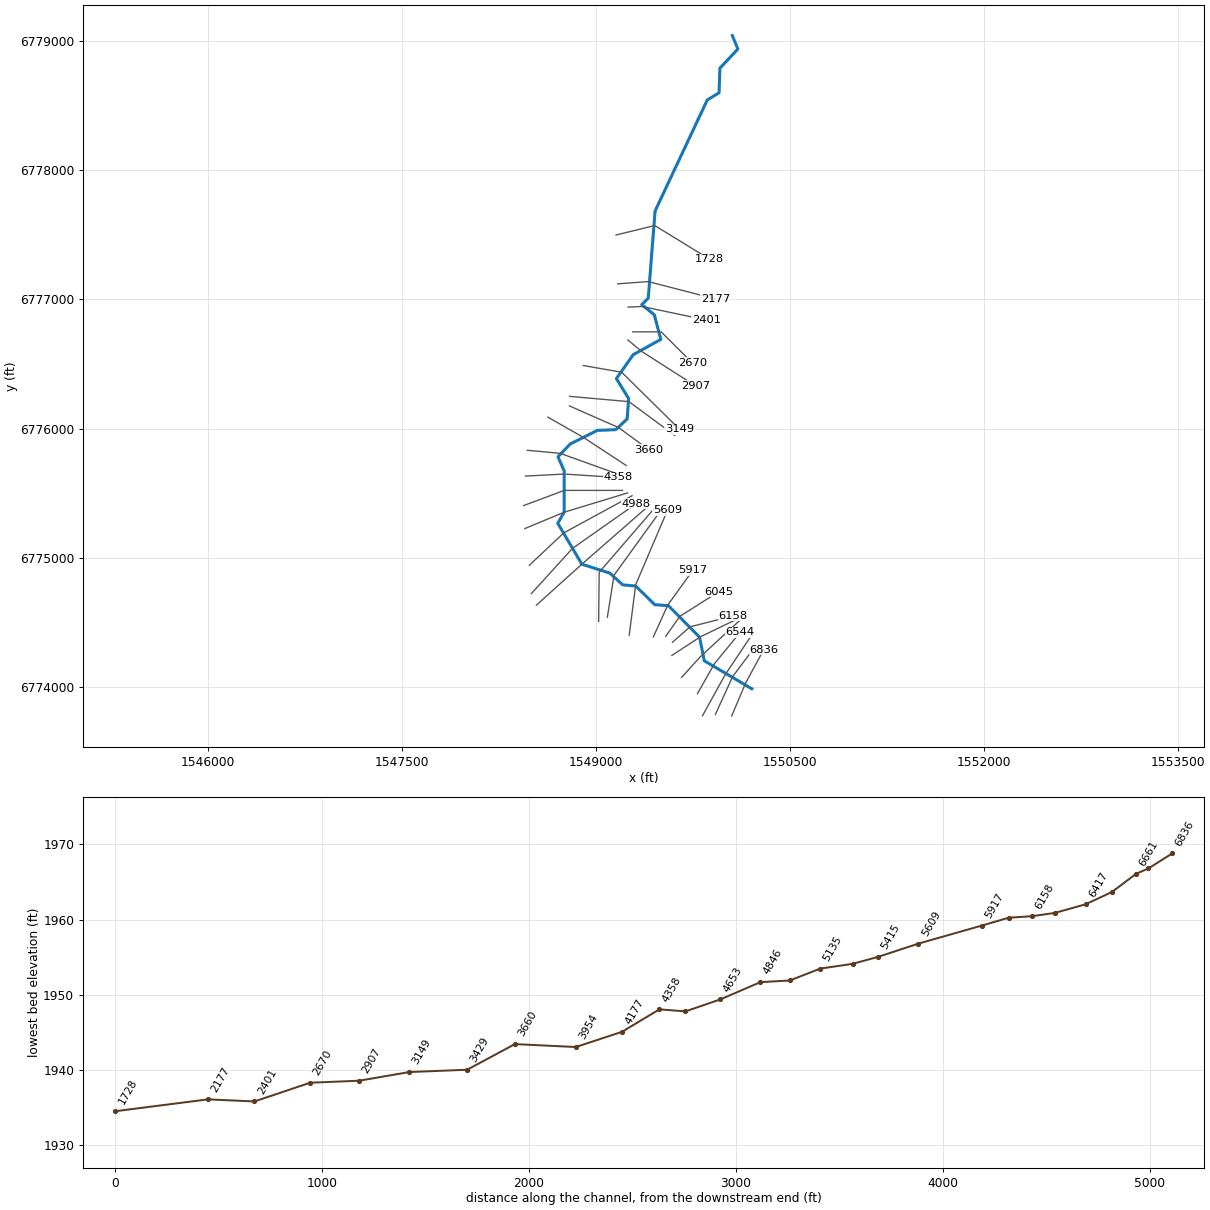
--- Elm 98.prj (project) ---

Proj Title=Elm 98 Base Level Engineering
Current Plan=p01
Default Exp/Contr=0.3,0.1
English Units
Geom File=g01
Flow File=f01
Plan File=p01
BEGIN DESCRIPTION:
Elm 98
END DESCRIPTION:

--- Elm 98.p01 (plan) ---

Plan Title=Multiple Run
Short Identifier=Multiple
Geom File=g01
Flow File=f01
Subcritical Flow
K Sum by GR= 0
Std Step Tol= 0.01
Critical Tol= 0.01
Num of Std Step Trials= 20
Max Error Tol= 0.3
Flow Tol Ratio= 0.001
Split Flow NTrial= 30
Split Flow Tol= 0.02
Split Flow Ratio= 0.02
Log Output Level= 0
Friction Slope Method= 1
Unsteady Friction Slope Method= 2
Unsteady Bridges Friction Slope Method= 1
Parabolic Critical Depth
Global Vel Dist=  1 , 1 , 1
Global Log Level= 0
CheckData=True
Encroach Param= -1, 0, 0, 0
BEGIN DESCRIPTION:
Multiple Run
END DESCRIPTION:

--- Elm 98.f01 (steady flow) ---

Flow Title=Multiple
Number of Profiles=7
Profile Names=10-year,25-year,50-year,1pct_min,100-year,1pct_plu,500-year
River Rch & RM= Elm 98,Reach-1,6836
      90     115     135      98     157     217     217
River Rch & RM= Elm 98,Reach-1,6417
     238     327     399     302     485     667     724
River Rch & RM= Elm 98,Reach-1,5609
     273     378     465     354     567     781     857
River Rch & RM= Elm 98,Reach-1,5135
     314     438     542     415     665     915    1010
Boundary for River Rch & Prof#=Elm 98,Reach-1,1
Up Type=0
Dn Type=3
Dn Slope=0.005
Boundary for River Rch & Prof#=Elm 98,Reach-1,2
Up Type=0
Dn Type=3
Dn Slope=0.005
Boundary for River Rch & Prof#=Elm 98,Reach-1,3
Up Type=0
Dn Type=3
Dn Slope=0.005
Boundary for River Rch & Prof#=Elm 98,Reach-1,4
Up Type=0
Dn Type=3
Dn Slope=0.005
Boundary for River Rch & Prof#=Elm 98,Reach-1,5
Up Type=0
Dn Type=3
Dn Slope=0.005
Boundary for River Rch & Prof#=Elm 98,Reach-1,6
Up Type=0
Dn Type=3
Dn Slope=0.005
Boundary for River Rch & Prof#=Elm 98,Reach-1,7
Up Type=0
Dn Type=3
Dn Slope=0.005

--- Elm 98.g01 (geometry) ---

Geom Title=Existing Conditions

River Reach=Elm 98,Reach-1
Reach XY= 30
      1550205.00      6773988.00      1549837.86      6774204.46
      1549801.46      6774386.53      1549561.22      6774630.26
      1549455.00      6774638.00      1549307.43      6774782.48
      1549206.50      6774791.63      1549107.43      6774882.48
      1548891.22      6774951.27      1548704.64      6775267.79
      1548754.46      6775353.21      1548754.46      6775672.79
      1548706.61      6775781.98      1548802.69      6775882.17
      1549010.93      6775985.75      1549153.54      6775991.54
      1549241.65      6776074.65      1549252.94      6776232.14
      1549158.31      6776386.27      1549288.29      6776571.37
      1549501.63      6776689.28      1549451.46      6776879.51
      1549354.56      6776958.25      1549404.67      6777008.28
      1549457.26      6777682.06      1549860.77      6778540.53
      1549951.91      6778596.31      1549958.54      6778786.53
      1550097.41      6778934.61      1550055.00      6779038.00

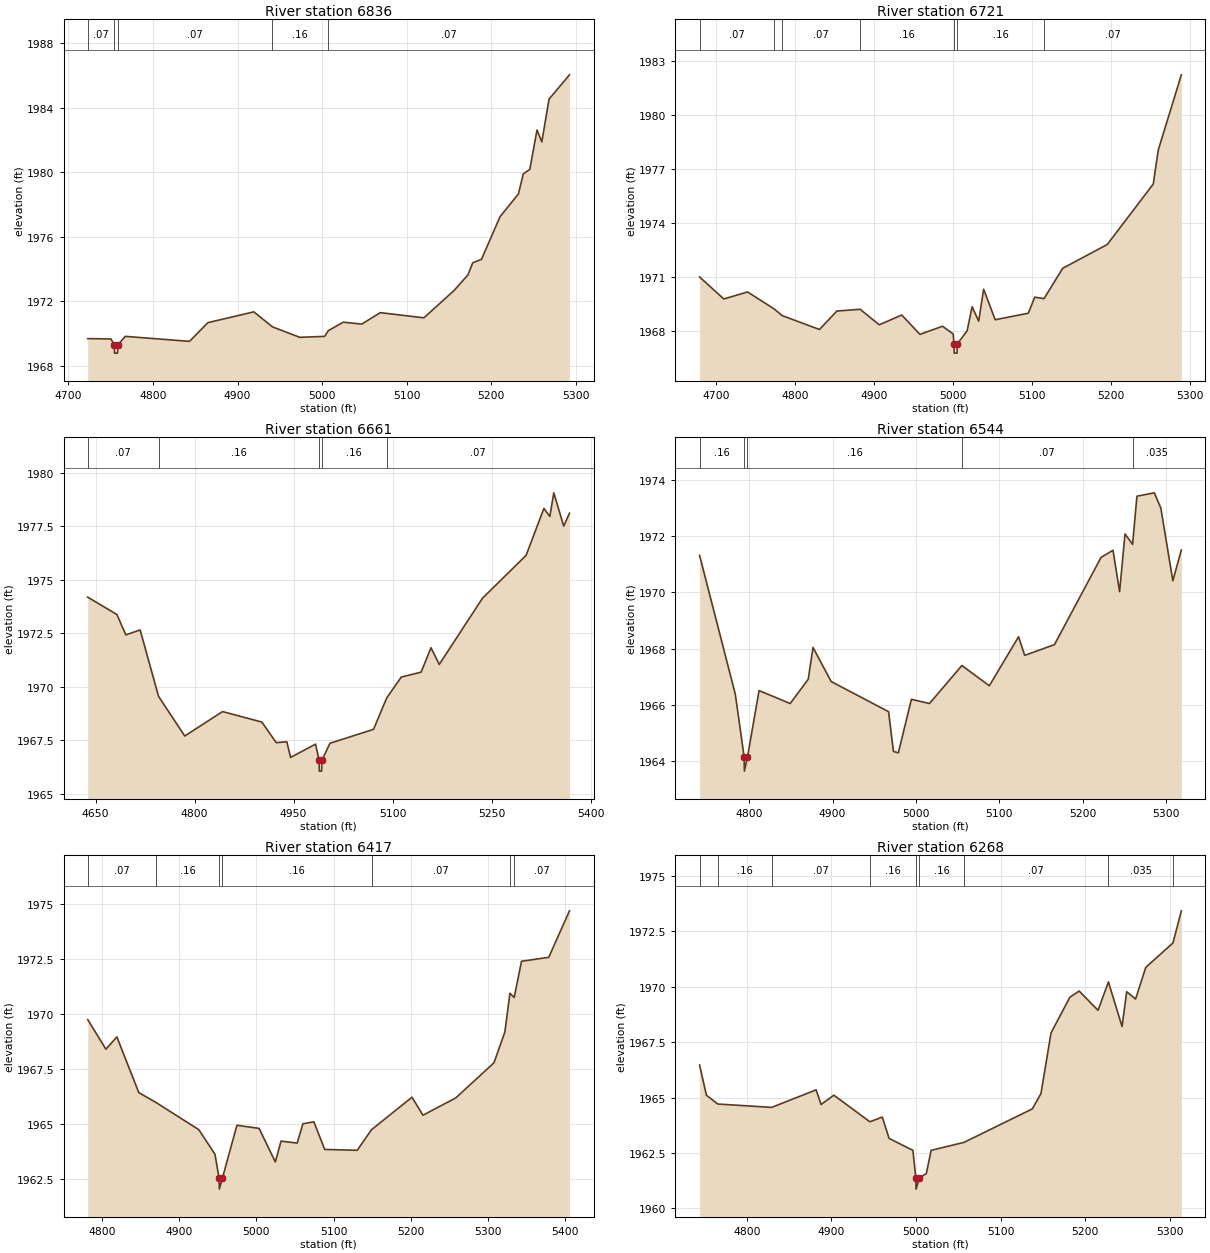
Type RM Length L Ch R = 1,6836,115,115,115
BEGIN DESCRIPTION:
Elm 98 3881
END DESCRIPTION:
XS GIS Cut Line= 3
      1550049.61      6773777.14      1550157.36      6774032.33
      1550296.98      6774289.24
#Sta/Elev= 30
  4723.0 1969.69  4750.4 1969.67  4754.5 1969.29  4754.7 1968.79  4758.2 1968.79
  4758.5 1969.29  4767.3 1969.83  4843.3 1969.52  4865.0 1970.68  4919.3 1971.35
  4941.3 1970.42  4973.6 1969.77  5003.1 1969.83  5007.2 1970.18  5025.0 1970.71
  5046.8 1970.59  5068.7 1971.30  5120.3 1970.98  5156.1 1972.68  5172.3 1973.64
  5178.0 1974.39  5188.4 1974.61  5210.3 1977.25  5232.1 1978.67  5237.8 1979.91
  5245.5 1980.19  5254.0 1982.63  5259.7 1981.89  5268.2 1984.54  5292.4 1986.05
#Mann=5,-1,0
  4723.0    0.07       0  4754.5    0.07       0  4758.5    0.07       0
  4941.3    0.16       0  5007.2    0.07       0
Bank Sta=4754.5,4758.5
Exp/Cntr=0.3,0.1

Type RM Length L Ch R = 1,6721,60,60,60
BEGIN DESCRIPTION:
Elm 98 3882
END DESCRIPTION:
XS GIS Cut Line= 3
      1549923.71      6773790.08      1550057.19      6774081.91
      1550230.02      6774313.03
#Sta/Elev= 30
  4679.1 1971.01  4709.8 1969.79  4739.8 1970.18  4773.1 1969.25  4783.6 1968.87
  4830.8 1968.10  4852.8 1969.12  4882.2 1969.22  4906.4 1968.36  4934.9 1968.90
  4957.9 1967.83  4986.5 1968.28  5000.0 1967.85  5001.0 1967.29  5001.3 1966.79
  5004.8 1966.79  5005.0 1967.29  5017.6 1968.03  5023.9 1969.36  5032.2 1968.56
  5038.5 1970.33  5053.1 1968.64  5095.0 1969.00  5103.1 1969.89  5114.9 1969.81
  5138.5 1971.49  5194.9 1972.81  5253.1 1976.16  5259.4 1978.04  5288.6 1982.21
#Mann=7,-1,0
  4679.1    0.07       0  4773.1    0.16       0  4783.6    0.07       0
  4882.2    0.16       0  5001.0    0.07       0  5005.0    0.16       0
  5114.9    0.07       0
Bank Sta=5001,5005
Exp/Cntr=0.3,0.1

Type RM Length L Ch R = 1,6661,117,117,117
BEGIN DESCRIPTION:
Elm 98 6660.945
END DESCRIPTION:
XS GIS Cut Line= 3
      1549823.91      6773779.29      1549998.95      6774096.16
      1550203.66      6774402.08
#Sta/Elev= 30
  4638.0 1974.19  4682.2 1973.38  4695.7 1972.43  4717.4 1972.66  4745.3 1969.56
  4785.0 1967.71  4842.3 1968.85  4901.9 1968.36  4923.6 1967.40  4939.7 1967.44
  4945.4 1966.71  4983.2 1967.33  4988.7 1966.57  4988.9 1966.07  4992.4 1966.07
  4992.7 1966.57  5005.1 1967.37  5071.1 1968.02  5091.0 1969.48  5113.1 1970.46
  5143.2 1970.69  5158.2 1971.83  5170.7 1971.05  5236.2 1974.14  5302.3 1976.14
  5329.3 1978.33  5338.3 1977.96  5344.3 1979.06  5359.3 1977.51  5368.1 1978.11
#Mann=5,-1,0
  4638.0    0.07       0  4745.3    0.16       0  4988.7    0.07       0
  4992.7    0.16       0  5091.0    0.07       0
Bank Sta=4988.7,4992.7
Exp/Cntr=0.3,0.1

Type RM Length L Ch R = 1,6544,127,127,127
BEGIN DESCRIPTION:
Elm 98 6543.74
END DESCRIPTION:
XS GIS Cut Line= 3
      1549784.83      6773950.70      1549917.21      6774182.92
      1550114.39      6774423.42
#Sta/Elev= 30
  4740.3 1971.31  4783.2 1966.38  4793.8 1964.15  4794.1 1963.65  4797.8 1964.15
  4811.7 1966.51  4849.1 1966.05  4870.7 1966.91  4876.5 1968.04  4898.3 1966.83
  4967.2 1965.76  4973.0 1964.35  4978.9 1964.30  4994.6 1966.20  5016.3 1966.05
  5055.2 1967.40  5088.1 1966.68  5123.2 1968.42  5130.6 1967.76  5166.3 1968.14
  5222.3 1971.24  5236.6 1971.49  5244.5 1970.02  5251.0 1972.07  5260.1 1971.70
  5265.3 1973.41  5286.2 1973.53  5294.0 1972.99  5308.4 1970.41  5318.6 1971.50
#Mann=5,-1,0
  4740.3    0.16       0  4793.8    0.07       0  4797.8    0.16       0
  5055.2    0.07       0  5260.1   0.035       0
Bank Sta=4793.8,4797.8
Exp/Cntr=0.3,0.1

Type RM Length L Ch R = 1,6417,149,149,149
BEGIN DESCRIPTION:
Elm 98 6416.86
END DESCRIPTION:
XS GIS Cut Line= 3
      1549663.32      6774076.59      1549808.71      6774237.17
      1550108.17      6774512.76
#Sta/Elev= 30
  4781.8 1969.75  4805.3 1968.40  4819.5 1968.96  4847.9 1966.42  4870.2 1965.97
  4925.6 1964.73  4946.5 1963.61  4951.8 1962.52  4952.1 1962.02  4956.1 1962.52
  4974.9 1964.93  5003.6 1964.79  5024.6 1963.26  5032.0 1964.21  5052.9 1964.12
  5060.3 1965.00  5074.5 1965.09  5088.5 1963.83  5130.6 1963.79  5149.1 1964.73
  5201.5 1966.21  5215.7 1965.39  5258.2 1966.18  5307.6 1967.78  5321.7 1969.18
  5328.3 1970.95  5333.8 1970.76  5343.3 1972.41  5378.5 1972.59  5405.4 1974.71
#Mann=7,-1,0
  4781.8    0.07       0  4870.2    0.16       0  4951.8    0.07       0
  4956.1    0.16       0  5149.1    0.07       0  5328.3   0.035       0
  5333.8    0.07       0
Bank Sta=4951.8,4956.1
Exp/Cntr=0.3,0.1

Type RM Length L Ch R = 1,6268,110,110,110
BEGIN DESCRIPTION:
Elm 98 6268.16
END DESCRIPTION:
XS GIS Cut Line= 3
      1549587.39      6774245.88      1549806.54      6774389.08
      1550083.65      6774523.31
#Sta/Elev= 30
  4744.1 1966.47  4752.2 1965.11  4765.7 1964.71  4829.4 1964.56  4881.9 1965.35
  4887.8 1964.69  4902.9 1965.11  4945.5 1963.91  4960.2 1964.12  4968.2 1963.16
  4996.4 1962.62  4999.8 1961.37  5000.1 1960.87  5004.1 1961.37  5012.3 1961.58
  5017.9 1962.62  5056.8 1962.98  5137.5 1964.49  5147.8 1965.18  5159.7 1967.92
  5182.0 1969.53  5193.0 1969.81  5215.3 1968.94  5227.6 1970.22  5243.7 1968.21
  5249.2 1969.78  5259.7 1969.45  5271.8 1970.88  5303.9 1971.98  5313.8 1973.43
#Mann=9,-1,0
  4744.1    0.07       0  4765.7    0.16       0  4829.4    0.07       0
  4945.5    0.16       0  4999.8    0.07       0  5004.1    0.16       0
  5056.8    0.07       0  5227.6   0.035       0  5303.9    0.07       0
Bank Sta=4999.8,5004.1
Exp/Cntr=0.3,0.1

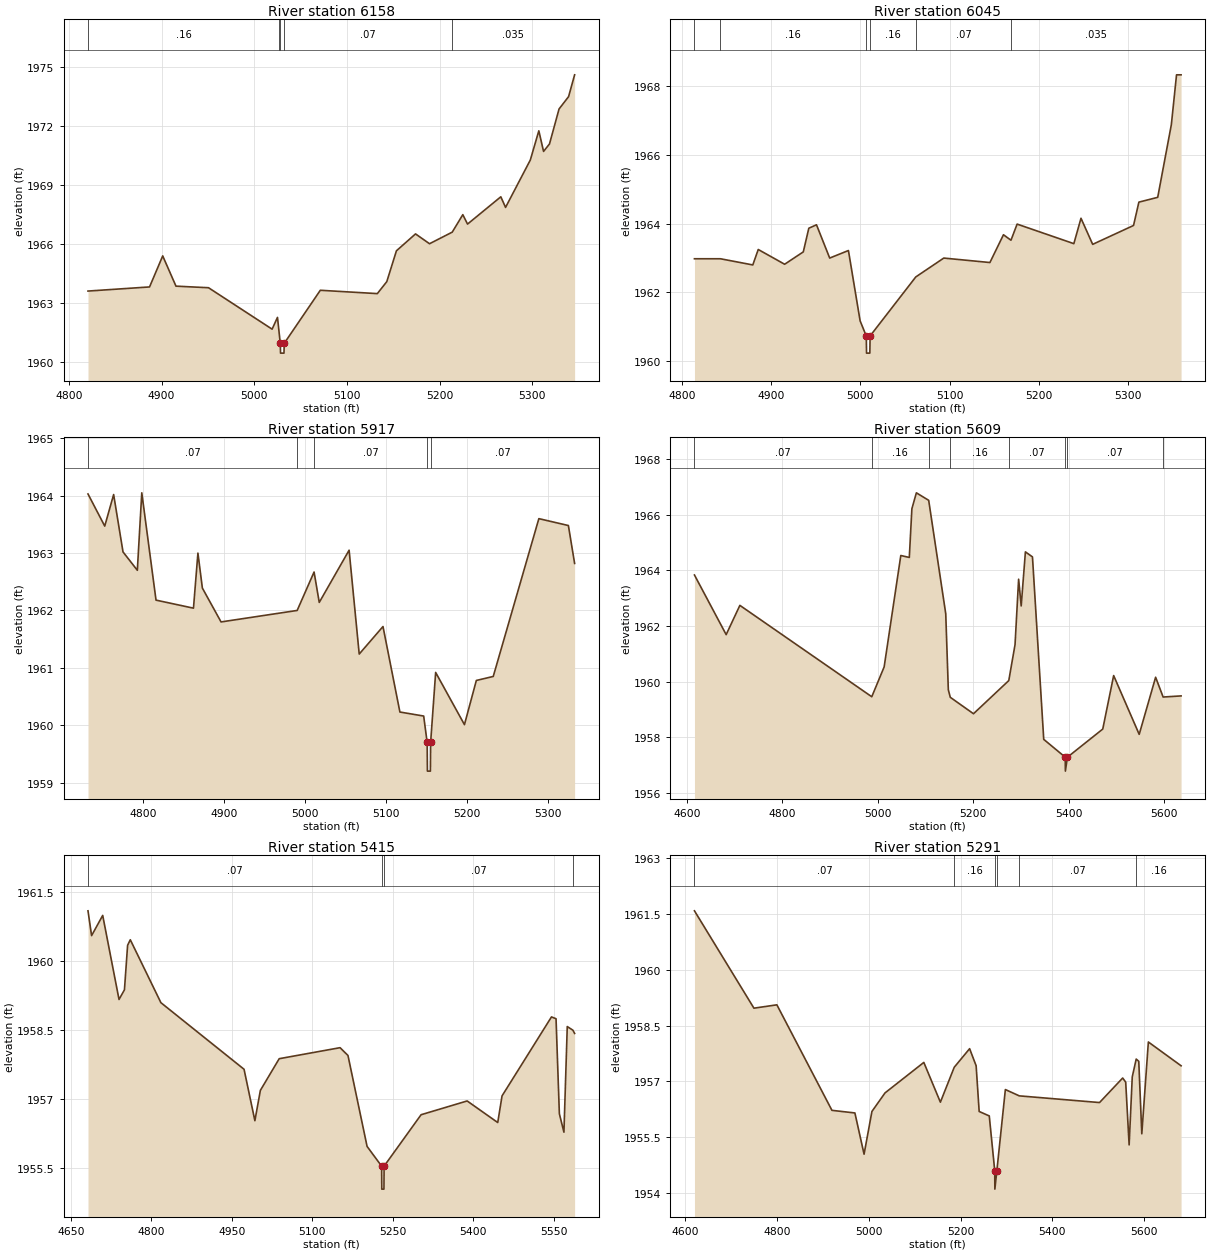
Type RM Length L Ch R = 1,6158,113,113,113
BEGIN DESCRIPTION:
Elm 98 6158.28
END DESCRIPTION:
XS GIS Cut Line= 3
      1549591.70      6774347.85      1549728.41      6774467.21
      1550061.32      6774551.51
#Sta/Elev= 30
  4820.7 1963.60  4887.1 1963.81  4901.3 1965.39  4915.6 1963.85  4950.7 1963.77
  5019.3 1961.66  5025.1 1962.26  5027.2 1961.34  5028.1 1960.94  5028.4 1960.44
  5032.1 1960.44  5032.4 1960.94  5071.3 1963.64  5132.8 1963.47  5143.0 1964.08
  5153.4 1965.65  5174.0 1966.51  5189.1 1966.01  5213.6 1966.60  5225.0 1967.49
  5230.1 1967.01  5266.0 1968.40  5271.1 1967.86  5297.8 1970.27  5307.0 1971.76
  5312.1 1970.71  5318.5 1971.09  5328.8 1972.87  5339.1 1973.50  5345.6 1974.61
#Mann=5,-1,0
  4820.7    0.16       0  5027.2    0.07       0  5028.1    0.07       0
  5032.4    0.07       0  5213.6   0.035       0
Bank Sta=5028.1,5032.4
Exp/Cntr=0.3,0.1

Type RM Length L Ch R = 1,6045,128,128,128
BEGIN DESCRIPTION:
Elm 98 6045.31
END DESCRIPTION:
XS GIS Cut Line= 3
      1549539.60      6774393.40      1549648.12      6774547.50
      1549949.77      6774738.48
#Sta/Elev= 30
  4814.1 1962.98  4843.2 1962.98  4879.5 1962.80  4885.6 1963.25  4915.2 1962.82
  4936.1 1963.18  4942.3 1963.87  4950.9 1963.97  4965.7 1963.00  4986.7 1963.22
  4999.8 1961.17  5006.7 1960.73  5007.0 1960.23  5010.7 1960.23  5011.0 1960.73
  5062.2 1962.45  5093.6 1963.00  5145.3 1962.87  5160.5 1963.68  5168.9 1963.52
  5175.8 1963.99  5239.4 1963.42  5247.4 1964.16  5260.5 1963.40  5306.3 1963.95
  5312.3 1964.63  5333.4 1964.77  5348.7 1966.89  5354.5 1968.34  5359.6 1968.34
#Mann=6,-1,0
  4814.1    0.07       0  4843.2    0.16       0  5006.7    0.07       0
  5011.0    0.16       0  5062.2    0.07       0  5168.9   0.035       0
Bank Sta=5006.7,5011
Exp/Cntr=0.3,0.1

Type RM Length L Ch R = 1,5917,308,308,308
BEGIN DESCRIPTION:
Elm 98 5917.38
END DESCRIPTION:
XS GIS Cut Line= 3
      1549444.14      6774389.12      1549554.80      6774634.31
      1549749.14      6774904.22
#Sta/Elev= 30
  4731.8 1964.03  4752.5 1963.47  4763.5 1964.02  4775.1 1963.02  4792.8 1962.70
  4798.3 1964.05  4815.9 1962.18  4862.2 1962.04  4867.7 1963.00  4873.2 1962.39
  4896.3 1961.80  4990.4 1962.00  5011.3 1962.67  5017.7 1962.14  5054.6 1963.05
  5067.1 1961.24  5096.5 1961.72  5117.4 1960.23  5146.8 1960.16  5151.1 1959.70
  5151.4 1959.20  5155.1 1959.20  5155.4 1959.70  5161.6 1960.92  5197.2 1960.01
  5211.9 1960.78  5232.8 1960.85  5289.2 1963.60  5325.7 1963.48  5333.4 1962.82
#Mann=5,-1,0
  4731.8    0.07       0  4990.4    0.16       0  5011.3    0.07       0
  5151.1    0.07       0  5155.4    0.07       0
Bank Sta=5151.1,5155.4
Exp/Cntr=0.3,0.1

Type RM Length L Ch R = 1,5609,194,194,194
BEGIN DESCRIPTION:
Elm 98 5609.17
END DESCRIPTION:
XS GIS Cut Line= 3
      1549257.50      6774402.14      1549307.40      6774792.73
      1549552.65      6775367.86
#Sta/Elev= 30
  4616.2 1963.83  4682.6 1961.69  4711.3 1962.74  4987.5 1959.46  5013.4 1960.53
  5048.3 1964.53  5066.1 1964.46  5071.5 1966.21  5080.9 1966.78  5106.7 1966.51
  5142.4 1962.44  5147.8 1959.71  5151.9 1959.44  5200.5 1958.85  5274.4 1960.04
  5287.5 1961.33  5295.0 1963.68  5300.4 1962.72  5309.2 1964.66  5324.0 1964.48
  5347.6 1957.93  5392.6 1957.29  5392.9 1956.79  5397.2 1957.29  5471.2 1958.30
  5494.0 1960.22  5547.5 1958.11  5581.9 1960.16  5597.6 1959.45  5635.2 1959.49
#Mann=8,-1,0
  4616.2    0.07       0  4987.5    0.16       0  5106.7    0.07       0
  5151.9    0.16       0  5274.4    0.07       0  5392.6    0.07       0
  5397.2    0.07       0  5597.6    0.16       0
Bank Sta=5392.6,5397.2
Exp/Cntr=0.3,0.1

Type RM Length L Ch R = 1,5415,124,124,124
BEGIN DESCRIPTION:
Elm 98 5415.38
END DESCRIPTION:
XS GIS Cut Line= 3
      1549088.22      6774540.97      1549140.30      6774866.51
      1549478.03      6775334.13
#Sta/Elev= 30
  4682.1 1961.09  4688.8 1960.55  4709.5 1960.99  4739.9 1959.16  4750.0 1959.37
  4755.9 1960.34  4760.9 1960.46  4817.9 1959.09  4972.8 1957.64  4993.0 1956.52
  5003.2 1957.18  5038.3 1957.87  5151.7 1958.11  5166.4 1957.94  5202.0 1955.96
  5229.1 1955.53  5229.4 1955.03  5233.4 1955.03  5233.7 1955.53  5302.6 1956.65
  5388.4 1956.95  5445.4 1956.48  5453.4 1957.06  5545.5 1958.78  5554.0 1958.74
  5560.2 1956.67  5568.7 1956.27  5574.9 1958.57  5585.5 1958.49  5588.6 1958.42
#Mann=4,-1,0
  4682.1    0.07       0  5229.1    0.07       0  5233.7    0.07       0
  5585.5    0.16       0
Bank Sta=5229.1,5233.7
Exp/Cntr=0.3,0.1

Type RM Length L Ch R = 1,5291,156,156,156
BEGIN DESCRIPTION:
Elm 98 5290.738
END DESCRIPTION:
XS GIS Cut Line= 3
      1549020.95      6774508.42      1549025.08      6774888.19
      1549469.37      6775403.78
#Sta/Elev= 30
  4620.2 1961.59  4749.8 1958.97  4799.8 1959.06  4919.8 1956.22  4969.8 1956.15
  4989.8 1955.04  5006.9 1956.19  5035.5 1956.69  5120.0 1957.51  5156.1 1956.44
  5186.3 1957.38  5219.8 1957.88  5234.0 1957.42  5240.6 1956.19  5262.6 1956.07
  5274.5 1954.60  5274.8 1954.10  5279.2 1954.60  5297.7 1956.78  5328.0 1956.61
  5502.9 1956.43  5553.3 1957.09  5559.9 1956.98  5567.4 1955.29  5574.2 1957.12
  5582.8 1957.60  5588.4 1957.54  5595.0 1955.59  5609.3 1958.06  5680.6 1957.42
#Mann=6,-1,0
  4620.2    0.07       0  5186.3    0.16       0  5274.5    0.07       0
  5279.2    0.16       0  5328.0    0.07       0  5582.8    0.16       0
Bank Sta=5274.5,5279.2
Exp/Cntr=0.3,0.1

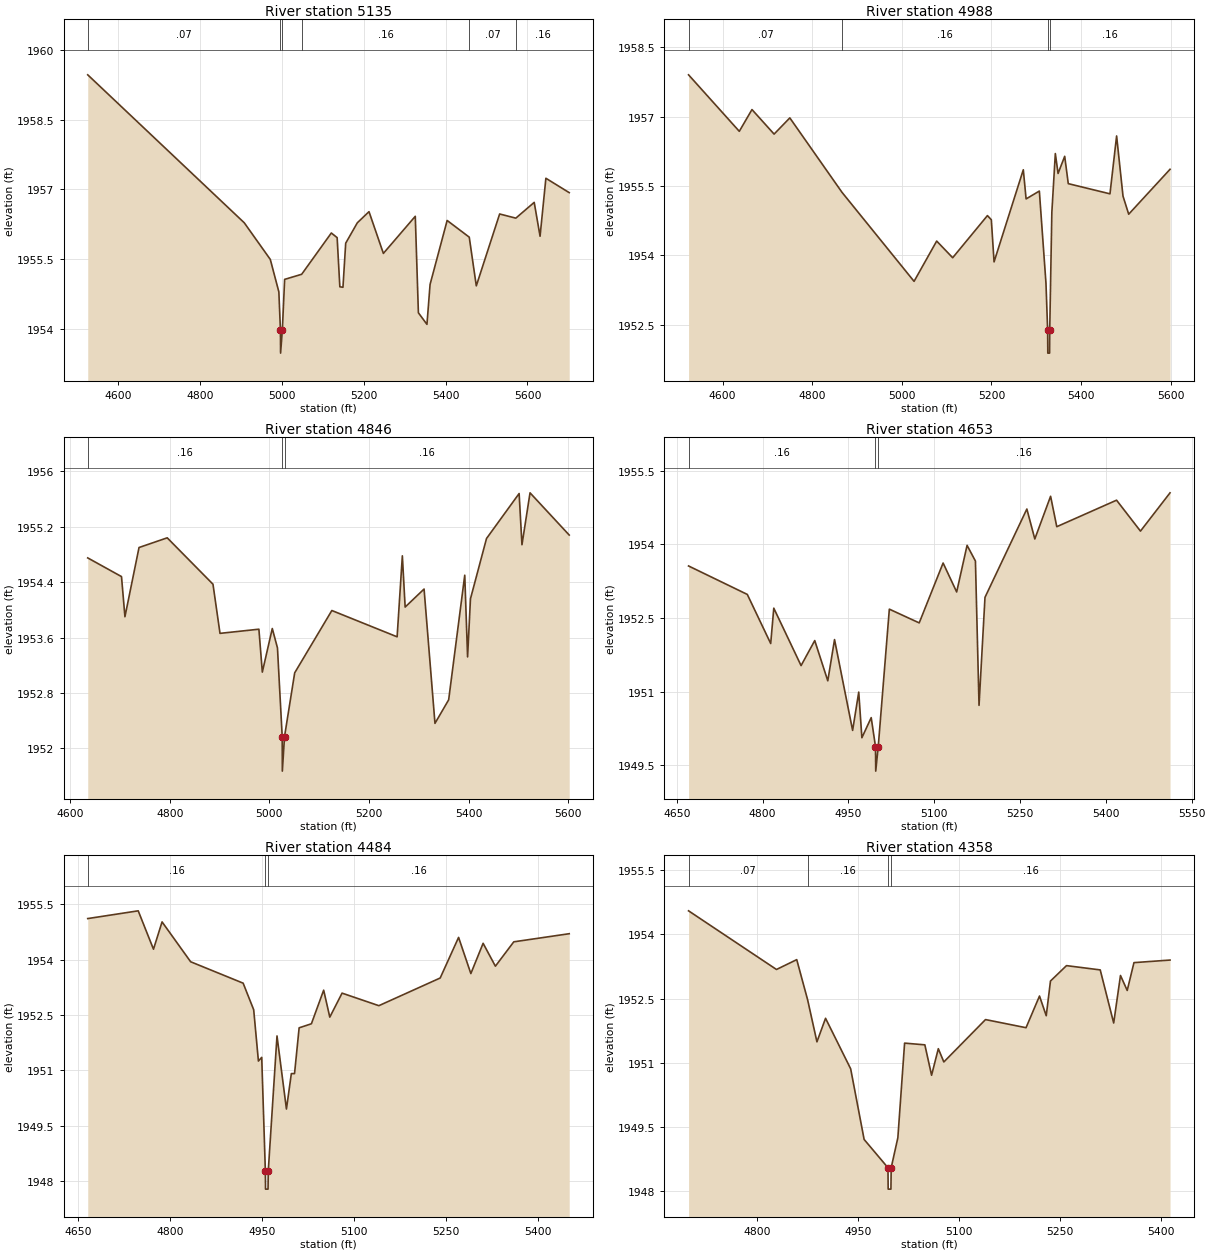
Type RM Length L Ch R = 1,5135,147,147,147
BEGIN DESCRIPTION:
Elm 98 3878
END DESCRIPTION:
XS GIS Cut Line= 3
      1548539.18      6774634.31      1548891.22      6774951.27
      1549419.78      6775413.25
#Sta/Elev= 30
  4526.3 1959.47  4908.5 1956.28  4972.1 1955.49  4993.0 1954.79  4996.8 1953.97
  4997.2 1953.47  5001.5 1953.97  5007.1 1955.06  5048.7 1955.17  5121.1 1956.06
  5135.3 1955.96  5141.9 1954.90  5149.5 1954.89  5156.2 1955.84  5184.6 1956.28
  5213.1 1956.52  5248.2 1955.62  5326.1 1956.42  5333.7 1954.34  5354.6 1954.09
  5362.2 1954.95  5403.9 1956.33  5457.9 1955.97  5475.1 1954.92  5532.1 1956.47
  5571.6 1956.38  5616.5 1956.72  5630.8 1955.99  5645.0 1957.24  5702.0 1956.93
#Mann=6,-1,0
  4526.3    0.07       0  4996.8    0.07       0  5001.5    0.07       0
  5048.7    0.16       0  5457.9    0.07       0  5571.6    0.16       0
Bank Sta=4996.8,5001.5
Exp/Cntr=0.3,0.1

Type RM Length L Ch R = 1,4988,142,142,142
BEGIN DESCRIPTION:
Elm 98 3877
END DESCRIPTION:
XS GIS Cut Line= 3
      1548500.09      6774723.26      1548818.29      6775073.03
      1549310.91      6775419.31
#Sta/Elev= 30
  4523.8 1957.90  4637.1 1956.68  4665.4 1957.15  4714.8 1956.62  4749.9 1956.97
  4866.6 1955.36  5027.3 1953.44  5077.8 1954.31  5113.5 1953.95  5191.1 1954.86
  5199.8 1954.77  5205.9 1953.86  5271.2 1955.85  5277.4 1955.22  5307.0 1955.39
  5321.8 1953.40  5325.5 1952.39  5325.9 1951.89  5329.9 1951.89  5330.2 1952.39
  5334.9 1954.93  5342.7 1956.20  5348.8 1955.77  5363.6 1956.14  5371.6 1955.55
  5464.7 1955.33  5479.5 1956.58  5493.8 1955.28  5506.5 1954.89  5598.8 1955.86
#Mann=4,-1,0
  4523.8    0.07       0  4866.6    0.16       0  5325.5    0.07       0
  5330.2    0.16       0
Bank Sta=5325.5,5330.2
Exp/Cntr=0.3,0.1

Type RM Length L Ch R = 1,4846,193,193,193
BEGIN DESCRIPTION:
Elm 98 3875
END DESCRIPTION:
XS GIS Cut Line= 3
      1548484.93      6774942.48      1548750.38      6775192.70
      1549279.17      6775480.65
#Sta/Elev= 30
  4635.2 1954.75  4703.0 1954.48  4709.9 1953.90  4738.2 1954.90  4794.8 1955.04
  4886.7 1954.37  4900.8 1953.66  4978.9 1953.72  4985.8 1953.10  5005.8 1953.73
  5016.2 1953.45  5025.7 1952.17  5026.0 1951.67  5030.4 1952.17  5050.8 1953.09
  5125.4 1953.99  5256.5 1953.61  5267.0 1954.78  5272.6 1954.04  5310.6 1954.30
  5332.5 1952.36  5360.0 1952.70  5392.3 1954.50  5398.0 1953.32  5403.8 1954.16
  5436.0 1955.03  5501.5 1955.68  5507.2 1954.94  5523.4 1955.69  5602.1 1955.08
#Mann=3,-1,0
  4635.2    0.16       0  5025.7    0.07       0  5030.4    0.16       0
Bank Sta=5025.7,5030.4
Exp/Cntr=0.3,0.1

Type RM Length L Ch R = 1,4653,169,169,169
BEGIN DESCRIPTION:
Elm 98 3874
END DESCRIPTION:
XS GIS Cut Line= 3
      1548450.19      6775226.75      1548754.46      6775353.21
      1549244.47      6775502.36
#Sta/Elev= 30
  4670.5 1953.56  4773.2 1952.98  4814.1 1951.98  4819.5 1952.70  4867.2 1951.53
  4891.1 1952.04  4913.9 1951.22  4925.7 1952.06  4957.3 1950.21  4968.0 1950.99
  4973.5 1950.06  4989.8 1950.47  4997.3 1949.88  4997.7 1949.38  5002.1 1949.88
  5021.5 1952.68  5073.7 1952.40  5115.5 1953.62  5139.2 1953.03  5157.4 1953.98
  5172.0 1953.66  5178.3 1950.72  5188.7 1952.92  5261.9 1954.72  5275.8 1954.11
  5303.4 1954.98  5314.2 1954.36  5418.7 1954.90  5460.5 1954.27  5512.2 1955.05
#Mann=3,-1,0
  4670.5    0.16       0  4997.3    0.07       0  5002.1    0.16       0
Bank Sta=4997.3,5002.1
Exp/Cntr=0.3,0.1

Type RM Length L Ch R = 1,4484,126,126,126
BEGIN DESCRIPTION:
Elm 98 3873
END DESCRIPTION:
XS GIS Cut Line= 3
      1548441.52      6775404.71      1548755.02      6775521.92
      1549205.42      6775521.89
#Sta/Elev= 30
  4665.3 1955.11  4747.6 1955.32  4772.5 1954.28  4786.5 1955.02  4833.1 1953.94
  4918.7 1953.36  4935.9 1952.64  4943.6 1951.25  4949.0 1951.35  4954.9 1948.28
  4955.2 1947.78  4959.3 1947.78  4959.7 1948.28  4973.9 1951.93  4989.3 1949.95
  4997.3 1950.91  5002.5 1950.91  5010.0 1952.15  5030.0 1952.26  5050.0 1953.17
  5060.0 1952.44  5080.0 1953.09  5140.0 1952.75  5240.0 1953.50  5270.0 1954.60
  5290.0 1953.62  5310.0 1954.44  5330.0 1953.82  5360.0 1954.48  5450.4 1954.70
#Mann=3,-1,0
  4665.3    0.16       0  4954.9    0.07       0  4959.7    0.16       0
Bank Sta=4954.9,4959.7
Exp/Cntr=0.3,0.1

Type RM Length L Ch R = 1,4358,181,181,181
BEGIN DESCRIPTION:
Elm 98 3872
END DESCRIPTION:
XS GIS Cut Line= 3
      1548454.55      6775632.57      1548755.45      6775648.19
      1549168.50      6775621.72
#Sta/Elev= 30
  4698.7 1954.55  4829.3 1953.18  4859.4 1953.41  4875.6 1952.47  4889.4 1951.49
  4902.2 1952.04  4939.5 1950.86  4959.5 1949.21  4994.9 1948.55  4995.2 1948.05
  4999.3 1948.05  4999.7 1948.55  5009.6 1949.25  5019.6 1951.46  5049.7 1951.42
  5059.7 1950.71  5069.7 1951.33  5077.9 1951.02  5139.8 1952.01  5200.0 1951.82
  5220.0 1952.56  5230.0 1952.10  5236.3 1952.91  5260.1 1953.27  5310.2 1953.17
  5330.2 1951.93  5340.3 1953.04  5350.3 1952.69  5360.3 1953.34  5413.9 1953.40
#Mann=4,-1,0
  4698.7    0.07       0  4875.6    0.16       0  4994.9    0.07       0
  4999.7    0.16       0
Bank Sta=4994.9,4999.7
Exp/Cntr=0.3,0.1

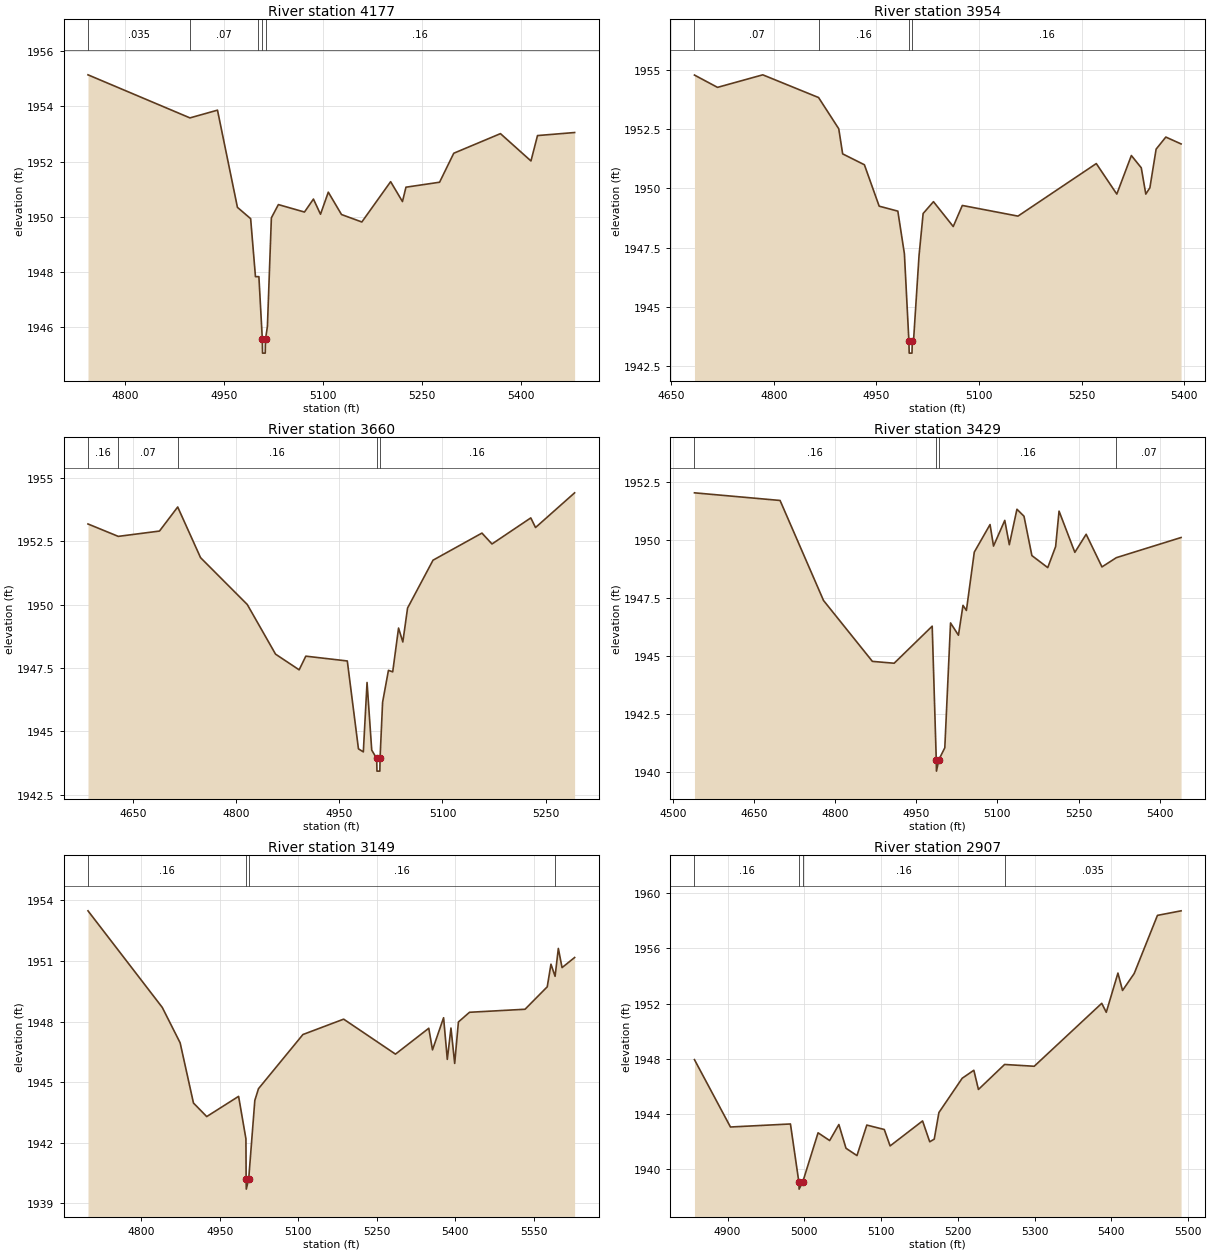
Type RM Length L Ch R = 1,4177,223,223,223
BEGIN DESCRIPTION:
Elm 98 3871
END DESCRIPTION:
XS GIS Cut Line= 3
      1548469.75      6775832.22      1548724.41      6775808.13
      1549177.22      6775645.58
#Sta/Elev= 30
  4744.2 1955.14  4898.6 1953.58  4940.3 1953.86  4970.5 1950.34  4990.5 1949.93
  4997.8 1947.83  5001.2 1947.83  5003.0 1947.83  5008.2 1945.56  5008.5 1945.06
  5012.6 1945.06  5013.0 1945.56  5015.9 1946.03  5021.9 1949.96  5032.5 1950.44
  5072.0 1950.17  5085.6 1950.64  5096.3 1950.09  5108.1 1950.89  5128.1 1950.08
  5158.9 1949.81  5202.5 1951.27  5220.4 1950.55  5225.7 1951.07  5276.6 1951.25
  5298.1 1952.30  5368.8 1953.01  5415.0 1952.02  5424.9 1952.94  5481.1 1953.05
#Mann=5,-1,0
  4744.2   0.035       0  4898.6    0.07       0  5001.2    0.16       0
  5008.2    0.07       0  5013.0    0.16       0
Bank Sta=5008.2,5013
Exp/Cntr=0.3,0.1

Type RM Length L Ch R = 1,3954,294,294,294
BEGIN DESCRIPTION:
Elm 98 3870
END DESCRIPTION:
XS GIS Cut Line= 3
      1548628.19      6776088.27      1548902.80      6775931.92
      1549233.64      6775715.02
#Sta/Elev= 30
  4684.0 1954.79  4717.7 1954.27  4783.9 1954.80  4865.5 1953.84  4895.0 1952.52
  4900.7 1951.46  4932.5 1951.00  4954.1 1949.25  4981.4 1949.04  4991.0 1947.24
  4997.6 1943.54  4998.0 1943.04  5002.1 1943.04  5002.5 1943.54  5004.3 1943.54
  5012.4 1947.16  5018.4 1948.94  5033.5 1949.44  5062.4 1948.39  5075.7 1949.28
  5157.1 1948.83  5271.6 1951.05  5301.6 1949.76  5322.9 1951.39  5337.4 1950.87
  5344.0 1949.76  5350.0 1950.03  5359.1 1951.66  5373.3 1952.17  5395.6 1951.88
#Mann=4,-1,0
  4684.0    0.07       0  4865.5    0.16       0  4997.6    0.07       0
  5002.5    0.16       0
Bank Sta=4997.6,5002.5
Exp/Cntr=0.3,0.1

Type RM Length L Ch R = 1,3660,231,231,231
BEGIN DESCRIPTION:
Elm 98 3869
END DESCRIPTION:
XS GIS Cut Line= 3
      1548795.29      6776175.09      1549175.21      6776007.59
      1549410.82      6775834.94
#Sta/Elev= 30
  4584.8 1953.19  4628.8 1952.70  4688.7 1952.91  4715.2 1953.86  4748.4 1951.86
  4816.3 1950.01  4857.4 1948.05  4891.7 1947.43  4901.4 1947.97  4961.7 1947.78
  4977.9 1944.31  4985.0 1944.19  4990.4 1946.93  4997.2 1944.26  5004.4 1943.93
  5004.8 1943.43  5009.0 1943.43  5009.3 1943.93  5013.0 1946.15  5021.5 1947.41
  5027.7 1947.35  5036.2 1949.08  5042.4 1948.53  5049.3 1949.87  5086.3 1951.76
  5157.4 1952.83  5172.0 1952.40  5228.4 1953.43  5235.3 1953.05  5292.1 1954.42
#Mann=5,-1,0
  4584.8    0.16       0  4628.8    0.07       0  4715.2    0.16       0
  5004.4    0.07       0  5009.3    0.16       0
Bank Sta=5004.4,5009.3
Exp/Cntr=0.3,0.1

Type RM Length L Ch R = 1,3429,280,280,280
BEGIN DESCRIPTION:
Elm 98 3868
END DESCRIPTION:
XS GIS Cut Line= 3
      1548797.47      6776248.89      1549255.46      6776208.16
      1549609.02      6775947.26
#Sta/Elev= 30
  4540.2 1952.04  4698.4 1951.71  4778.7 1947.39  4869.0 1944.76  4909.2 1944.68
  4979.5 1946.28  4987.0 1940.52  4987.4 1940.02  4991.9 1940.52  5002.8 1941.03
  5013.4 1946.42  5028.0 1945.89  5036.4 1947.18  5042.7 1946.96  5057.3 1949.48
  5086.4 1950.67  5092.8 1949.74  5113.6 1950.85  5122.0 1949.80  5136.1 1951.33
  5149.1 1951.03  5163.7 1949.33  5193.0 1948.81  5207.6 1949.72  5213.9 1951.25
  5243.1 1949.47  5264.0 1950.25  5293.2 1948.84  5319.8 1949.24  5439.4 1950.11
#Mann=4,-1,0
  4540.2    0.16       0  4987.0    0.07       0  4991.9    0.16       0
  5319.8    0.07       0
Bank Sta=4987,4991.9
Exp/Cntr=0.3,0.1

Type RM Length L Ch R = 1,3149,242,242,242
BEGIN DESCRIPTION:
Elm 98 3867
END DESCRIPTION:
XS GIS Cut Line= 3
      1548901.60      6776487.60      1549198.82      6776435.81
      1549645.95      6775994.98
#Sta/Elev= 30
  4698.3 1953.48  4840.2 1948.70  4874.3 1946.95  4899.8 1943.97  4925.1 1943.30
  4986.0 1944.30  5000.0 1942.20  5000.4 1940.21  5000.7 1939.71  5005.3 1940.21
  5017.0 1944.10  5024.0 1944.68  5108.9 1947.36  5186.7 1948.12  5285.7 1946.39
  5349.3 1947.67  5356.4 1946.60  5377.6 1948.19  5384.7 1946.13  5391.7 1947.68
  5398.8 1945.93  5405.9 1947.98  5427.1 1948.46  5533.2 1948.61  5575.6 1949.72
  5582.7 1950.84  5590.6 1950.24  5596.8 1951.62  5603.9 1950.67  5627.9 1951.17
#Mann=4,-1,0
  4698.3    0.16       0  5000.4    0.07       0  5005.3    0.16       0
  5590.6    0.07       0
Bank Sta=5000.4,5005.3
Exp/Cntr=0.3,0.1

Type RM Length L Ch R = 1,2907,237,237,237
BEGIN DESCRIPTION:
Elm 98 3866
END DESCRIPTION:
XS GIS Cut Line= 3
      1549246.62      6776685.10      1549357.19      6776594.10
      1549770.94      6776329.74
#Sta/Elev= 30
  4856.8 1947.94  4903.7 1943.06  4981.9 1943.28  4992.9 1939.06  4993.2 1938.56
  4997.8 1939.06  5017.9 1942.64  5033.0 1942.08  5045.0 1943.24  5054.3 1941.52
  5068.6 1940.99  5081.4 1943.20  5104.2 1942.88  5111.8 1941.69  5154.1 1943.50
  5163.4 1941.99  5169.3 1942.18  5175.4 1944.11  5205.7 1946.59  5220.9 1947.17
  5226.9 1945.78  5261.0 1947.59  5299.6 1947.46  5387.6 1952.02  5393.5 1951.37
  5408.7 1954.21  5414.7 1952.95  5429.9 1954.18  5460.2 1958.39  5491.0 1958.72
#Mann=4,-1,0
  4856.8    0.16       0  4992.9    0.07       0  4997.8    0.16       0
  5261.0   0.035       0
Bank Sta=4992.9,4997.8
Exp/Cntr=0.3,0.1

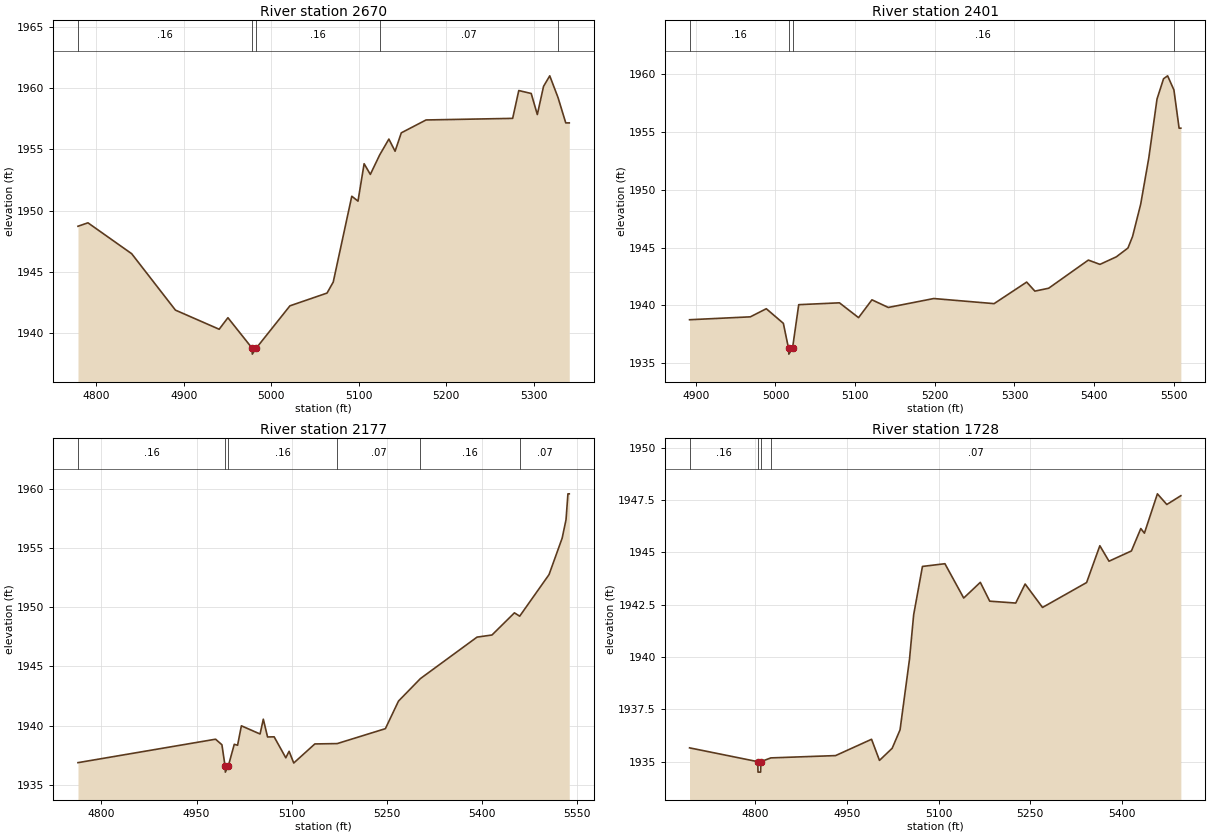
Type RM Length L Ch R = 1,2670,269,269,269
BEGIN DESCRIPTION:
Elm 98 3865
END DESCRIPTION:
XS GIS Cut Line= 3
      1549283.57      6776748.02      1549504.57      6776747.68
      1549745.74      6776507.17
#Sta/Elev= 30
  4779.0 1948.72  4790.4 1949.00  4840.4 1946.48  4890.4 1941.88  4940.4 1940.32
  4950.4 1941.26  4977.9 1938.79  4978.3 1938.29  4982.9 1938.79  5021.3 1942.23
  5063.7 1943.27  5070.8 1944.17  5092.0 1951.17  5099.1 1950.77  5106.1 1953.82
  5113.2 1952.95  5123.9 1954.54  5134.4 1955.83  5141.5 1954.84  5148.6 1956.34
  5176.9 1957.39  5275.9 1957.52  5282.9 1959.79  5297.1 1959.55  5304.1 1957.83
  5311.2 1960.13  5318.3 1960.99  5327.8 1959.21  5336.6 1957.15  5340.6 1957.15
#Mann=5,-1,0
  4779.0    0.16       0  4977.9    0.07       0  4982.9    0.16       0
  5123.9    0.07       0  5327.8   0.035       0
Bank Sta=4977.9,4982.9
Exp/Cntr=0.3,0.1

Type RM Length L Ch R = 1,2401,224,224,224
BEGIN DESCRIPTION:
Elm 98 3863
END DESCRIPTION:
XS GIS Cut Line= 3
      1549248.79      6776938.99      1549356.46      6776944.22
      1549854.30      6776839.16
#Sta/Elev= 30
  4892.2 1938.77  4968.5 1939.02  4988.5 1939.72  5009.9 1938.46  5016.4 1936.30
  5016.8 1935.80  5021.4 1936.30  5029.2 1940.07  5080.3 1940.23  5104.3 1938.95
  5121.1 1940.49  5141.6 1939.83  5198.7 1940.60  5274.4 1940.16  5315.3 1942.02
  5325.6 1941.24  5342.9 1941.49  5392.7 1943.92  5407.3 1943.55  5427.8 1944.20
  5442.4 1944.96  5448.2 1945.96  5458.4 1948.75  5468.6 1952.75  5478.9 1957.83
  5487.1 1959.58  5492.2 1959.83  5500.1 1958.61  5506.6 1955.31  5508.8 1955.31
#Mann=4,-1,0
  4892.2    0.16       0  5016.4    0.07       0  5021.4    0.16       0
  5500.1    0.07       0
Bank Sta=5016.4,5021.4
Exp/Cntr=0.3,0.1

Type RM Length L Ch R = 1,2177,449,449,449
BEGIN DESCRIPTION:
Elm 98 3861
END DESCRIPTION:
XS GIS Cut Line= 3
      1549168.47      6777119.11      1549404.84      6777136.47
      1549925.85      6777001.94
#Sta/Elev= 30
  4763.0 1936.88  4980.1 1938.86  4990.1 1938.39  4995.1 1936.58  4995.5 1936.08
  5000.1 1936.58  5009.6 1938.43  5014.8 1938.35  5020.8 1939.99  5050.3 1939.30
  5055.4 1940.55  5062.1 1939.05  5072.5 1939.06  5090.9 1937.29  5096.1 1937.84
  5103.4 1936.85  5136.7 1938.46  5172.0 1938.49  5248.0 1939.75  5268.7 1942.08
  5303.3 1943.98  5392.6 1947.48  5416.2 1947.66  5451.6 1949.53  5459.9 1949.25
  5506.2 1952.76  5526.9 1955.84  5533.0 1957.40  5536.0 1959.58  5538.1 1959.58
#Mann=6,-1,0
  4763.0    0.16       0  4995.1    0.07       0  5000.1    0.16       0
  5172.0    0.07       0  5303.3    0.16       0  5459.9    0.07       0
Bank Sta=4995.1,5000.1
Exp/Cntr=0.3,0.1

Type RM Length L Ch R = 1,1728,0,0,0
BEGIN DESCRIPTION:
Elm 98 3859
END DESCRIPTION:
XS GIS Cut Line= 3
      1549155.45      6777496.71      1549454.54      6777569.86
      1549878.14      6777310.10
#Sta/Elev= 30
  4692.1 1935.66  4803.8 1935.00  4804.2 1934.50  4808.5 1934.50  4808.9 1935.00
  4825.2 1935.18  4931.3 1935.29  4990.2 1936.07  5003.2 1935.06  5024.0 1935.64
  5036.9 1936.52  5052.4 1939.90  5059.2 1942.02  5073.6 1944.33  5110.4 1944.46
  5141.2 1942.82  5168.4 1943.57  5183.8 1942.67  5226.4 1942.58  5241.8 1943.49
  5270.3 1942.37  5342.5 1943.56  5364.2 1945.32  5379.2 1944.58  5415.9 1945.07
  5431.3 1946.14  5437.2 1945.92  5458.5 1947.80  5473.9 1947.29  5496.9 1947.71
#Mann=4,-1,0
  4692.1    0.16       0  4803.8    0.07       0  4808.9    0.16       0
  4825.2    0.07       0
Bank Sta=4803.8,4808.9
Exp/Cntr=0.3,0.1

Chan Stop Cuts=-1