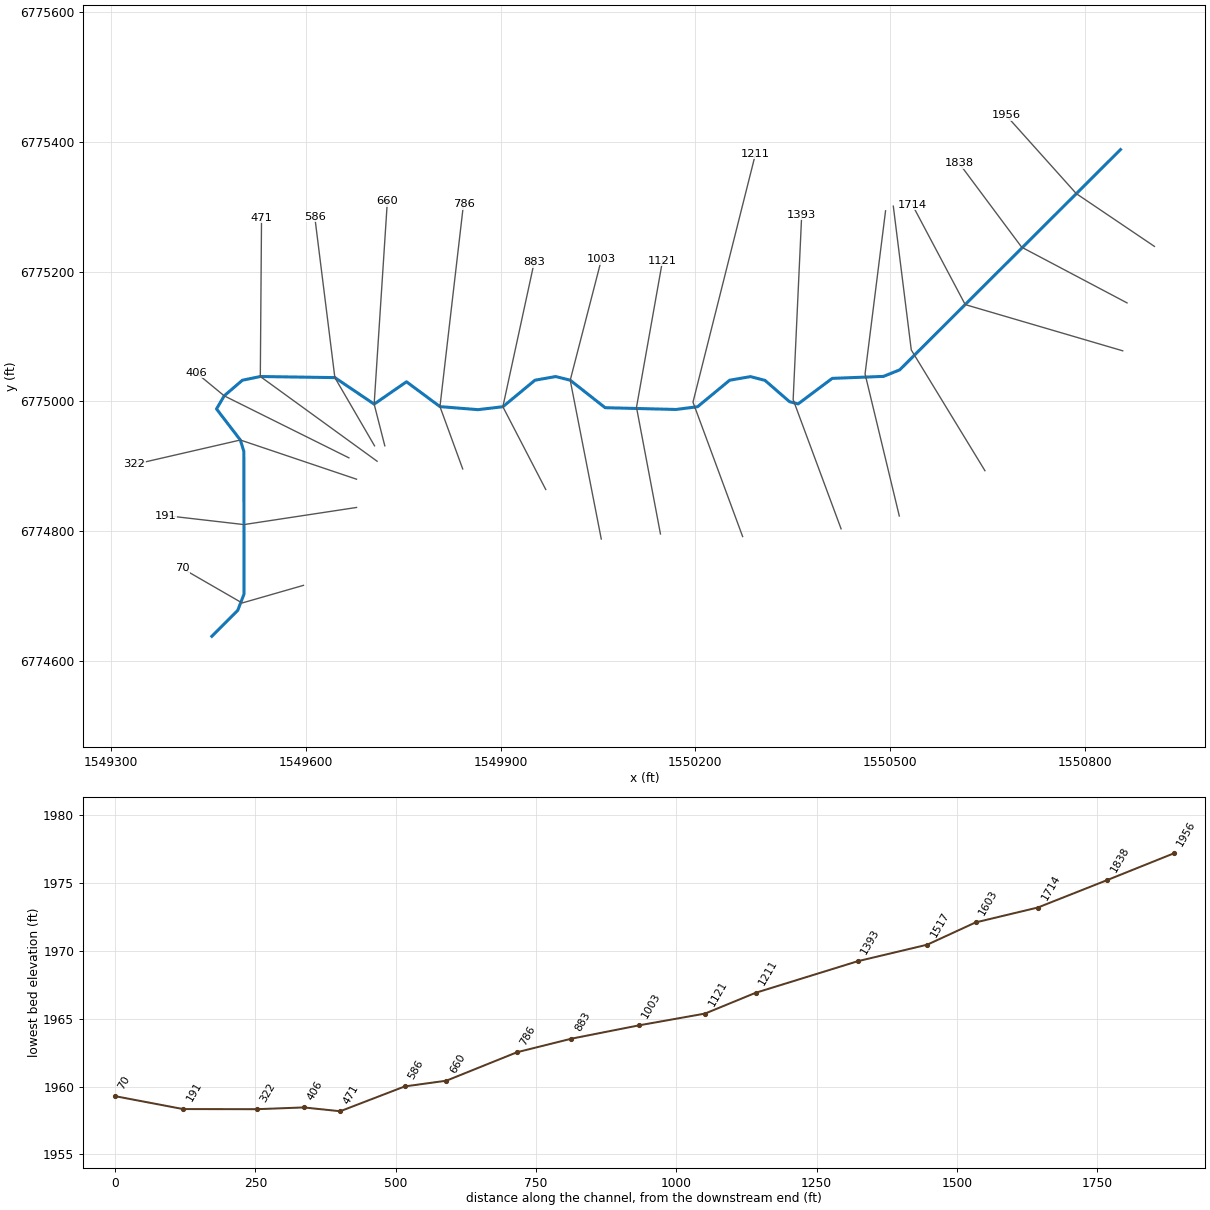
--- Elm 99.prj (project) ---

Proj Title=Elm 99 Base Level Engineering
Current Plan=p01
Default Exp/Contr=0.3,0.1
English Units
Geom File=g01
Flow File=f01
Plan File=p01
BEGIN DESCRIPTION:
Elm 99
END DESCRIPTION:

--- Elm 99.p01 (plan) ---

Plan Title=Multiple Run
Short Identifier=Multiple
Geom File=g01
Flow File=f01
Subcritical Flow
K Sum by GR= 0
Std Step Tol= 0.01
Critical Tol= 0.01
Num of Std Step Trials= 20
Max Error Tol= 0.3
Flow Tol Ratio= 0.001
Split Flow NTrial= 30
Split Flow Tol= 0.02
Split Flow Ratio= 0.02
Log Output Level= 0
Friction Slope Method= 1
Unsteady Friction Slope Method= 2
Unsteady Bridges Friction Slope Method= 1
Parabolic Critical Depth
Global Vel Dist=  1 , 1 , 1
Global Log Level= 0
CheckData=True
Encroach Param= -1, 0, 0, 0
BEGIN DESCRIPTION:
Multiple Run
END DESCRIPTION:

--- Elm 99.f01 (steady flow) ---

Flow Title=Multiple
Number of Profiles=7
Profile Names=10-year,25-year,50-year,1pct_min,100-year,1pct_plu,500-year
River Rch & RM= Elm 99,Reach-1,1956
      72      93     108      79     127     175     175
Boundary for River Rch & Prof#=Elm 99,Reach-1,1
Up Type=0
Dn Type=3
Dn Slope=0.005
Boundary for River Rch & Prof#=Elm 99,Reach-1,2
Up Type=0
Dn Type=3
Dn Slope=0.005
Boundary for River Rch & Prof#=Elm 99,Reach-1,3
Up Type=0
Dn Type=3
Dn Slope=0.005
Boundary for River Rch & Prof#=Elm 99,Reach-1,4
Up Type=0
Dn Type=3
Dn Slope=0.005
Boundary for River Rch & Prof#=Elm 99,Reach-1,5
Up Type=0
Dn Type=3
Dn Slope=0.005
Boundary for River Rch & Prof#=Elm 99,Reach-1,6
Up Type=0
Dn Type=3
Dn Slope=0.005
Boundary for River Rch & Prof#=Elm 99,Reach-1,7
Up Type=0
Dn Type=3
Dn Slope=0.005

--- Elm 99.g01 (geometry) ---

Geom Title=Existing Conditions

River Reach=Elm 99,Reach-1
Reach XY= 30
      1550855.00      6775388.00      1550514.79      6775048.52
      1550489.78      6775038.51      1550410.90      6775035.45
      1550358.29      6774996.10      1550345.07      6774999.53
      1550307.29      6775032.35      1550284.87      6775038.17
      1550252.83      6775032.60      1550203.44      6774991.80
      1550170.16      6774987.54      1550060.93      6774990.28
      1550007.18      6775032.62      1549984.82      6775038.28
      1549952.82      6775032.62      1549903.41      6774991.74
      1549865.05      6774987.25      1549806.50      6774991.93
      1549754.90      6775030.20      1549705.10      6774995.79
      1549644.56      6775036.64      1549529.70      6775038.32
      1549501.99      6775032.55      1549474.09      6775008.53
      1549462.21      6774988.35      1549498.96      6774940.47
      1549504.33      6774922.85      1549504.64      6774703.15
      1549494.95      6774678.02      1549455.00      6774638.00

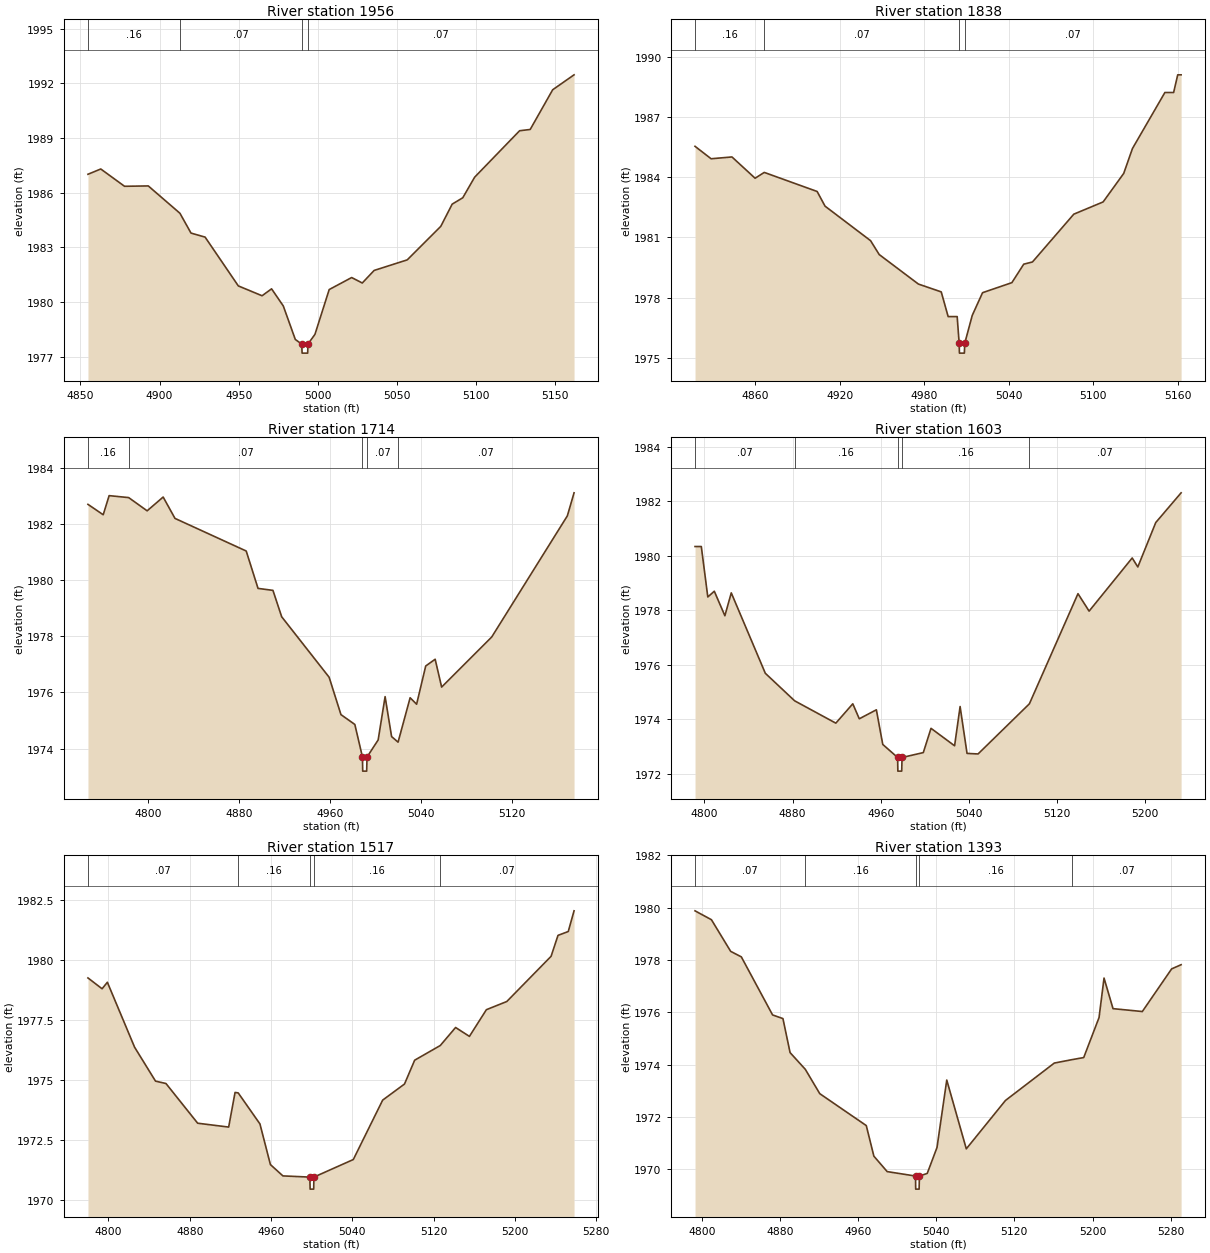
Type RM Length L Ch R = 1,1956,118,118,118
BEGIN DESCRIPTION:
Elm 99 1955.657
END DESCRIPTION:
XS GIS Cut Line= 3
      1550907.27      6775238.82      1550786.96      6775320.10
      1550678.91      6775440.67
#Sta/Elev= 30
  4854.8 1987.01  4862.9 1987.30  4877.9 1986.35  4892.9 1986.37  4912.9 1984.87
  4919.9 1983.78  4928.8 1983.56  4949.8 1980.88  4964.8 1980.34  4970.8 1980.72
  4978.2 1979.78  4985.8 1977.94  4989.8 1977.69  4990.1 1977.19  4993.6 1977.19
  4993.8 1977.69  4998.2 1978.22  5007.2 1980.68  5021.4 1981.34  5028.1 1981.04
  5035.6 1981.73  5056.5 1982.31  5077.7 1984.15  5084.9 1985.37  5091.6 1985.72
  5099.1 1986.85  5127.5 1989.40  5134.2 1989.47  5148.4 1991.65  5161.9 1992.47
#Mann=4,-1,0
  4854.8    0.16       0  4912.9    0.07       0  4989.8    0.07       0
  4993.8    0.07       0
Bank Sta=4989.8,4993.8
Exp/Cntr=0.3,0.1

Type RM Length L Ch R = 1,1838,124,124,124
BEGIN DESCRIPTION:
Elm 99 1838.06
END DESCRIPTION:
XS GIS Cut Line= 3
      1550865.07      6775151.77      1550702.82      6775237.51
      1550606.53      6775366.78
#Sta/Elev= 30
  4817.5 1985.53  4828.9 1984.91  4843.7 1985.00  4860.1 1983.94  4866.6 1984.23
  4904.1 1983.28  4909.7 1982.55  4942.0 1980.83  4948.1 1980.14  4975.9 1978.67
  4992.1 1978.28  4997.0 1977.05  5003.4 1977.05  5004.8 1975.73  5005.0 1975.23
  5008.5 1975.23  5008.8 1975.73  5014.1 1977.11  5021.4 1978.24  5042.2 1978.74
  5050.6 1979.66  5056.8 1979.77  5086.1 1982.15  5106.9 1982.76  5121.5 1984.18
  5127.7 1985.42  5150.7 1988.21  5156.9 1988.21  5159.8 1989.09  5162.2 1989.09
#Mann=4,-1,0
  4817.5    0.16       0  4866.6    0.07       0  5004.8    0.07       0
  5008.8    0.07       0
Bank Sta=5004.8,5008.8
Exp/Cntr=0.3,0.1

Type RM Length L Ch R = 1,1714,111,111,111
BEGIN DESCRIPTION:
Elm 99 1713.75
END DESCRIPTION:
XS GIS Cut Line= 3
      1550858.43      6775077.93      1550615.77      6775149.14
      1550534.11      6775303.25
#Sta/Elev= 30
  4747.0 1982.69  4760.4 1982.32  4765.6 1983.00  4782.8 1982.93  4799.0 1982.46
  4813.1 1982.95  4823.5 1982.19  4886.1 1981.03  4896.5 1979.70  4909.6 1979.63
  4917.3 1978.69  4959.0 1976.54  4969.4 1975.21  4981.6 1974.86  4988.3 1973.70
  4988.5 1973.20  4992.0 1973.20  4992.3 1973.70  5002.1 1974.31  5008.2 1975.85
  5013.9 1974.43  5019.6 1974.23  5030.2 1975.81  5035.9 1975.58  5043.9 1976.94
  5052.2 1977.18  5057.9 1976.19  5101.9 1977.97  5168.4 1982.28  5174.3 1983.10
#Mann=5,-1,0
  4747.0    0.16       0  4782.8    0.07       0  4988.3    0.07       0
  4992.3    0.07       0  5019.6    0.07       0
Bank Sta=4988.3,4992.3
Exp/Cntr=0.3,0.1

Type RM Length L Ch R = 1,1603,86,86,86
BEGIN DESCRIPTION:
Elm 99 1603.33
END DESCRIPTION:
XS GIS Cut Line= 3
      1550646.12      6774893.23      1550532.67      6775079.24
      1550504.97      6775300.84
#Sta/Elev= 30
  4791.5 1980.34  4797.2 1980.34  4803.1 1978.49  4809.0 1978.70  4818.6 1977.80
  4824.4 1978.64  4855.3 1975.69  4881.9 1974.68  4919.3 1973.86  4934.7 1974.57
  4940.6 1974.02  4956.1 1974.35  4961.9 1973.08  4975.4 1972.60  4975.6 1972.10
  4979.1 1972.10  4979.4 1972.60  4998.7 1972.78  5005.7 1973.67  5027.1 1973.03
  5032.1 1974.47  5038.4 1972.75  5048.4 1972.73  5095.0 1974.57  5139.1 1978.61
  5149.2 1977.97  5188.3 1979.92  5193.4 1979.59  5209.7 1981.22  5232.7 1982.31
#Mann=5,-1,0
  4791.5    0.07       0  4881.9    0.16       0  4975.4    0.07       0
  4979.4    0.16       0  5095.0    0.07       0
Bank Sta=4975.4,4979.4
Exp/Cntr=0.3,0.1

Type RM Length L Ch R = 1,1517,124,124,124
BEGIN DESCRIPTION:
Elm 99 1516.68
END DESCRIPTION:
XS GIS Cut Line= 3
      1550514.20      6774823.38      1550461.45      6775042.31
      1550493.03      6775293.64
#Sta/Elev= 30
  4779.8 1979.24  4793.7 1978.79  4798.9 1979.06  4825.7 1976.36  4846.3 1974.95
  4856.6 1974.85  4887.8 1973.20  4918.3 1973.04  4924.6 1974.48  4927.7 1974.46
  4949.1 1973.17  4959.4 1971.48  4971.7 1971.01  4998.2 1970.96  4998.5 1970.46
  5002.0 1970.46  5002.2 1970.96  5041.0 1971.69  5069.9 1974.16  5091.4 1974.83
  5101.4 1975.82  5126.6 1976.43  5141.7 1977.18  5155.3 1976.81  5172.0 1977.92
  5192.1 1978.26  5235.7 1980.14  5242.5 1981.01  5252.6 1981.17  5258.3 1982.03
#Mann=5,-1,0
  4779.8    0.07       0  4927.7    0.16       0  4998.2    0.07       0
  5002.2    0.16       0  5126.6    0.07       0
Bank Sta=4998.2,5002.2
Exp/Cntr=0.3,0.1

Type RM Length L Ch R = 1,1393,182,182,182
BEGIN DESCRIPTION:
Elm 99 1393.03
END DESCRIPTION:
XS GIS Cut Line= 3
      1550424.51      6774803.60      1550350.66      6775002.74
      1550363.85      6775287.64
#Sta/Elev= 30
  4793.1 1979.88  4809.9 1979.54  4829.6 1978.33  4840.5 1978.12  4872.5 1975.90
  4883.1 1975.76  4890.4 1974.46  4906.0 1973.82  4920.8 1972.89  4968.4 1971.67
  4976.2 1970.50  4989.8 1969.91  5018.8 1969.74  5019.0 1969.24  5022.5 1969.24
  5022.8 1969.74  5030.8 1969.84  5040.8 1970.83  5050.8 1973.41  5070.8 1970.78
  5110.9 1972.63  5160.9 1974.06  5179.0 1974.19  5191.0 1974.27  5206.7 1975.80
  5211.8 1977.31  5221.0 1976.14  5251.0 1976.03  5281.0 1977.66  5290.7 1977.82
#Mann=5,-1,0
  4793.1    0.07       0  4906.0    0.16       0  5018.8    0.07       0
  5022.8    0.16       0  5179.0    0.07       0
Bank Sta=5018.8,5022.8
Exp/Cntr=0.3,0.1

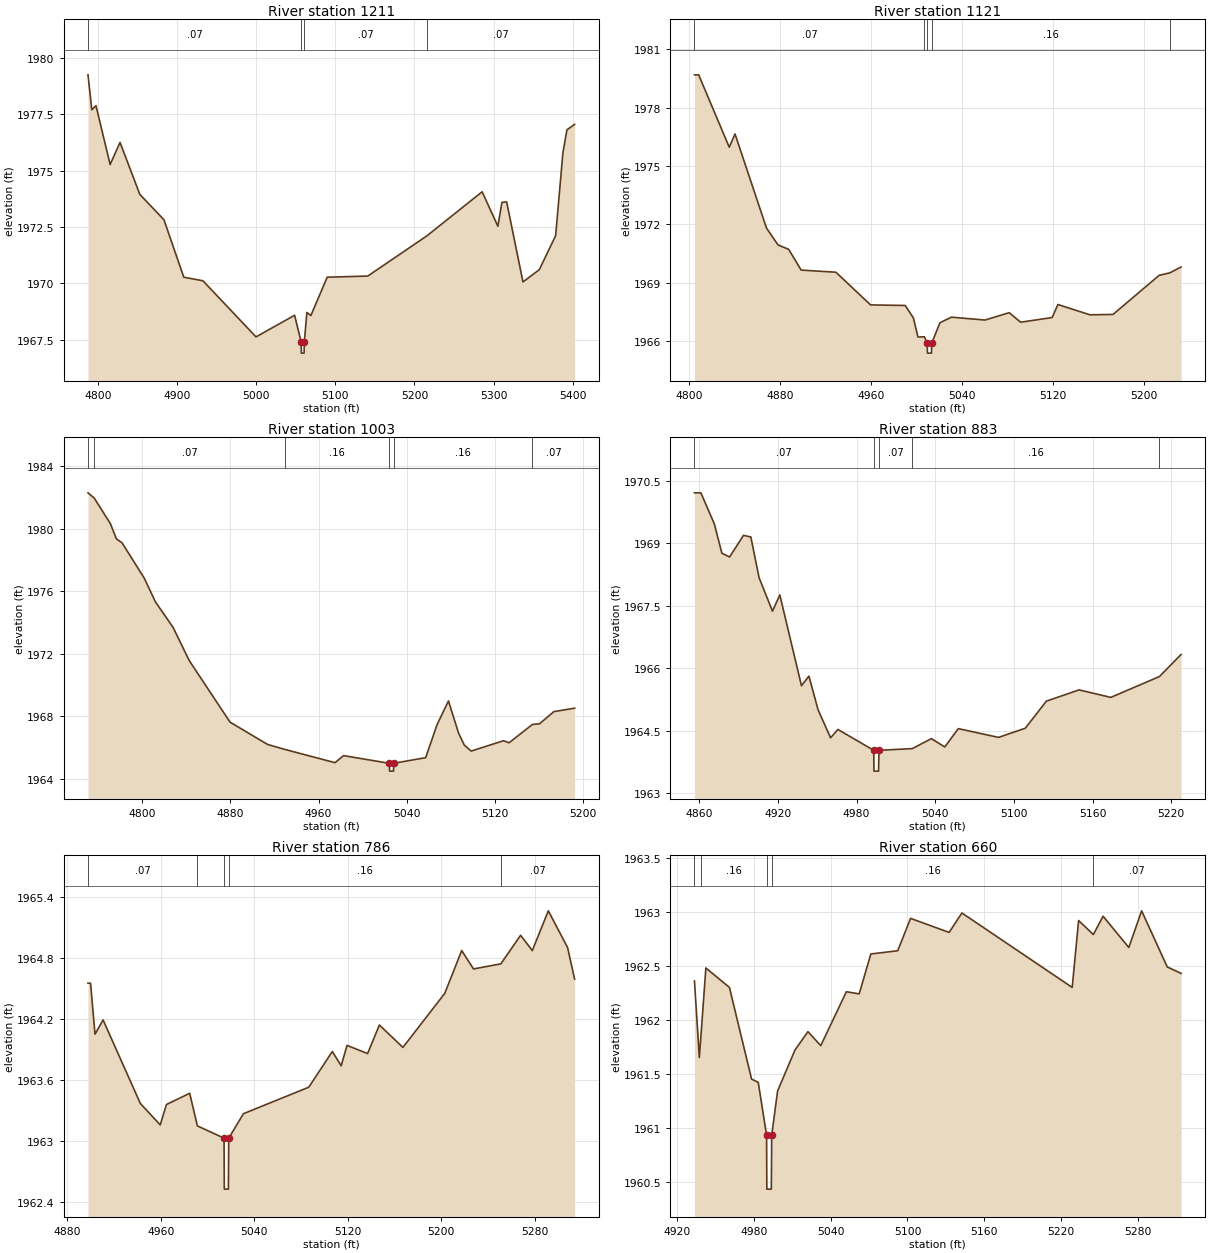
Type RM Length L Ch R = 1,1211,90,90,90
BEGIN DESCRIPTION:
Elm 99 1210.81
END DESCRIPTION:
XS GIS Cut Line= 3
      1550272.83      6774791.73      1550196.34      6774998.78
      1550292.63      6775381.32
#Sta/Elev= 30
  4787.3 1979.26  4792.1 1977.71  4797.4 1977.89  4815.3 1975.28  4827.8 1976.26
  4852.9 1973.95  4883.3 1972.83  4908.4 1970.28  4932.6 1970.12  4999.7 1967.63
  5048.5 1968.59  5056.8 1967.41  5057.0 1966.91  5060.5 1966.91  5060.8 1967.41
  5064.0 1968.71  5069.1 1968.58  5089.7 1970.28  5141.0 1970.33  5215.6 1972.11
  5285.6 1974.07  5305.5 1972.54  5310.6 1973.60  5316.6 1973.62  5337.2 1970.07
  5357.8 1970.61  5378.5 1972.12  5387.7 1975.80  5392.8 1976.82  5402.5 1977.06
#Mann=4,-1,0
  4787.3    0.07       0  5056.8    0.07       0  5060.8    0.07       0
  5215.6    0.07       0
Bank Sta=5056.8,5060.8
Exp/Cntr=0.3,0.1

Type RM Length L Ch R = 1,1121,118,118,118
BEGIN DESCRIPTION:
Elm 99 1121.35
END DESCRIPTION:
XS GIS Cut Line= 3
      1550146.21      6774795.70      1550109.29      6774990.87
      1550149.45      6775217.00
#Sta/Elev= 30
  4804.7 1979.69  4808.4 1979.69  4835.3 1975.97  4840.4 1976.65  4868.1 1971.81
  4878.3 1970.94  4887.6 1970.72  4898.6 1969.65  4929.2 1969.54  4959.7 1967.86
  4990.2 1967.83  4997.4 1967.19  5001.4 1966.21  5007.1 1966.22  5009.5 1965.88
  5009.8 1965.38  5013.3 1965.38  5013.5 1965.88  5020.7 1966.94  5030.9 1967.23
  5060.4 1967.08  5081.7 1967.46  5091.8 1966.97  5119.5 1967.21  5124.6 1967.88
  5152.8 1967.35  5173.1 1967.37  5213.7 1969.38  5223.2 1969.51  5233.0 1969.81
#Mann=5,-1,0
  4804.7    0.07       0  5007.1    0.16       0  5009.5    0.07       0
  5013.5    0.16       0  5223.2    0.07       0
Bank Sta=5009.5,5013.5
Exp/Cntr=0.3,0.1

Type RM Length L Ch R = 1,1003,120,120,120
BEGIN DESCRIPTION:
Elm 99 1003.492
END DESCRIPTION:
XS GIS Cut Line= 3
      1550055.01      6774787.95      1550007.18      6775032.62
      1550055.29      6775218.91
#Sta/Elev= 30
  4750.7 1982.28  4756.3 1981.95  4771.1 1980.30  4776.5 1979.34  4781.6 1979.09
  4801.7 1976.84  4811.9 1975.32  4828.0 1973.68  4842.5 1971.58  4879.6 1967.64
  4913.8 1966.21  4929.2 1965.90  4974.9 1965.05  4982.7 1965.50  5024.2 1965.01
  5024.5 1964.51  5028.0 1964.51  5028.2 1965.01  5057.2 1965.37  5067.5 1967.47
  5077.9 1968.99  5087.1 1966.93  5092.3 1966.17  5098.5 1965.79  5127.8 1966.45
  5132.9 1966.32  5154.1 1967.49  5160.5 1967.53  5173.6 1968.31  5192.4 1968.53
#Mann=6,-1,0
  4750.7   0.035       0  4756.3    0.07       0  4929.2    0.16       0
  5024.2    0.07       0  5028.2    0.16       0  5154.1    0.07       0
Bank Sta=5024.2,5028.2
Exp/Cntr=0.3,0.1

Type RM Length L Ch R = 1,883,97,97,97
BEGIN DESCRIPTION:
Elm 99 4021
END DESCRIPTION:
XS GIS Cut Line= 3
      1549969.48      6774864.24      1549903.41      6774991.74
      1549951.64      6775214.07
#Sta/Elev= 30
  4856.4 1970.21  4861.3 1970.21  4871.6 1969.46  4877.3 1968.76  4883.2 1968.67
  4893.8 1969.19  4899.4 1969.15  4905.7 1968.17  4915.9 1967.37  4921.5 1967.76
  4938.0 1965.58  4943.7 1965.81  4950.7 1965.00  4960.2 1964.33  4965.8 1964.53
  4993.1 1964.03  4993.3 1963.53  4996.8 1963.53  4997.1 1964.03  5022.5 1964.07
  5037.1 1964.31  5047.3 1964.11  5057.6 1964.55  5088.3 1964.34  5108.7 1964.56
  5124.8 1965.21  5149.7 1965.48  5173.9 1965.30  5211.0 1965.80  5227.5 1966.33
#Mann=5,-1,0
  4856.4    0.07       0  4993.1    0.07       0  4997.1    0.07       0
  5022.5    0.16       0  5211.0    0.07       0
Bank Sta=4993.1,4997.1
Exp/Cntr=0.3,0.1

Type RM Length L Ch R = 1,786,126,126,126
BEGIN DESCRIPTION:
Elm 99 4020
END DESCRIPTION:
XS GIS Cut Line= 3
      1549841.53      6774895.92      1549806.50      6774991.93
      1549842.76      6775303.93
#Sta/Elev= 30
  4897.8 1964.55  4900.0 1964.55  4903.8 1964.05  4910.7 1964.19  4942.6 1963.37
  4959.6 1963.16  4964.9 1963.36  4984.8 1963.47  4991.4 1963.15  5014.2 1963.03
  5014.4 1962.53  5017.9 1962.53  5018.2 1963.03  5030.8 1963.27  5086.7 1963.53
  5106.8 1963.88  5114.4 1963.74  5119.4 1963.94  5137.0 1963.86  5147.1 1964.14
  5167.2 1963.92  5203.0 1964.45  5217.5 1964.87  5227.6 1964.69  5251.0 1964.74
  5267.9 1965.02  5277.9 1964.87  5291.6 1965.26  5308.1 1964.90  5314.1 1964.59
#Mann=5,-1,0
  4897.8    0.07       0  4991.4    0.16       0  5014.2    0.07       0
  5018.2    0.16       0  5251.0    0.07       0
Bank Sta=5014.2,5018.2
Exp/Cntr=0.3,0.1

Type RM Length L Ch R = 1,660,74,74,74
BEGIN DESCRIPTION:
Elm 99 4017
END DESCRIPTION:
XS GIS Cut Line= 3
      1549721.50      6774931.56      1549705.10      6774995.79
      1549725.47      6775308.73
#Sta/Elev= 30
  4933.7 1962.36  4937.5 1961.65  4939.0 1961.89  4942.6 1962.48  4961.0 1962.30
  4978.3 1961.45  4983.5 1961.42  4990.0 1960.93  4990.2 1960.43  4993.7 1960.43
  4994.0 1960.93  4998.6 1961.34  5012.2 1961.72  5022.3 1961.89  5032.3 1961.76
  5052.3 1962.26  5062.3 1962.24  5071.4 1962.61  5092.4 1962.64  5102.4 1962.94
  5132.5 1962.81  5142.5 1962.99  5228.6 1962.30  5233.6 1962.92  5245.1 1962.79
  5252.7 1962.96  5272.8 1962.67  5282.8 1963.01  5302.8 1962.49  5313.6 1962.43
#Mann=5,-1,0
  4933.7    0.07       0  4939.0    0.16       0  4990.0    0.07       0
  4994.0    0.16       0  5245.1    0.07       0
Bank Sta=4990,4994
Exp/Cntr=0.3,0.1

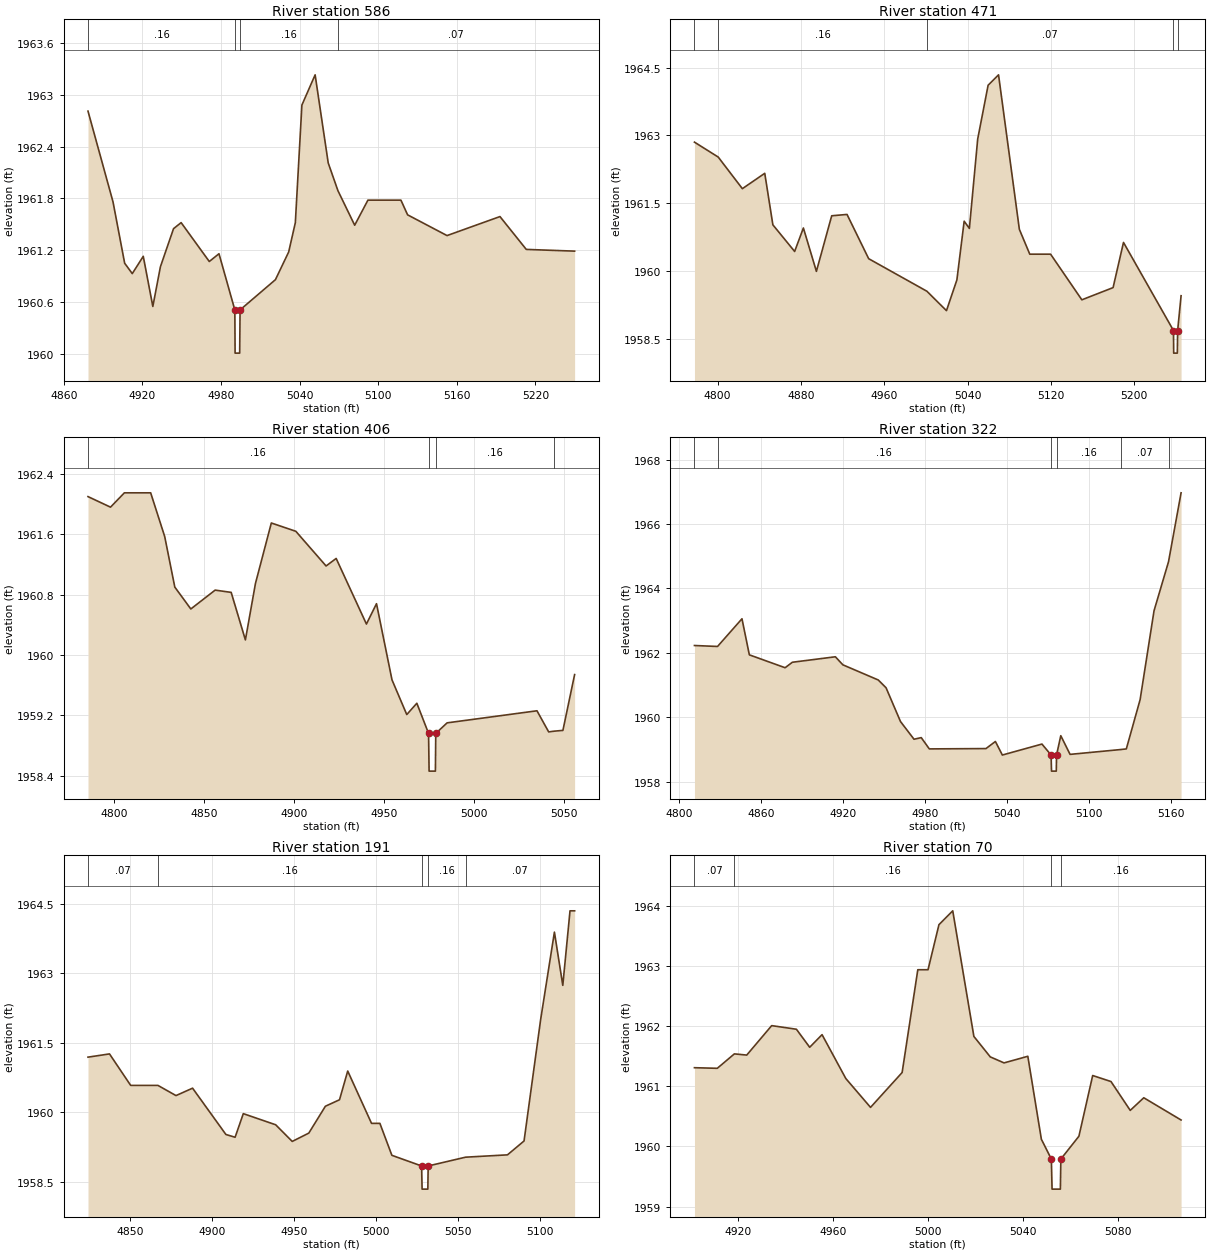
Type RM Length L Ch R = 1,586,115,115,115
BEGIN DESCRIPTION:
Elm 99 4018
END DESCRIPTION:
XS GIS Cut Line= 3
      1549705.68      6774931.52      1549644.56      6775036.64
      1549613.57      6775284.61
#Sta/Elev= 30
  4878.4 1962.81  4897.5 1961.76  4906.4 1961.05  4912.2 1960.93  4920.6 1961.13
  4927.9 1960.55  4933.7 1961.01  4943.7 1961.45  4949.5 1961.52  4971.0 1961.07
  4978.4 1961.16  4990.5 1960.51  4990.7 1960.01  4994.2 1960.01  4994.5 1960.51
  5021.5 1960.86  5031.6 1961.18  5036.7 1961.52  5041.7 1962.88  5051.8 1963.23
  5061.8 1962.21  5069.2 1961.89  5082.0 1961.49  5092.1 1961.78  5117.3 1961.78
  5122.4 1961.61  5152.5 1961.37  5192.9 1961.59  5213.0 1961.21  5249.9 1961.19
#Mann=4,-1,0
  4878.4    0.16       0  4990.5    0.07       0  4994.5    0.16       0
  5069.2    0.07       0
Bank Sta=4990.5,4994.5
Exp/Cntr=0.3,0.1

Type RM Length L Ch R = 1,471,65,65,65
BEGIN DESCRIPTION:
Elm 99 4015
END DESCRIPTION:
XS GIS Cut Line= 3
      1549709.63      6774907.78      1549529.70      6775038.32
      1549531.58      6775283.31
#Sta/Elev= 30
  4777.7 1962.85  4800.5 1962.52  4823.7 1961.82  4845.2 1962.16  4853.0 1961.02
  4873.9 1960.43  4882.3 1960.95  4894.8 1959.99  4909.5 1961.22  4924.2 1961.25
  4945.0 1960.27  5000.9 1959.55  5019.7 1959.12  5029.7 1959.80  5036.7 1961.10
  5041.7 1960.94  5049.7 1962.92  5059.7 1964.11  5069.7 1964.34  5089.7 1960.92
  5099.7 1960.37  5119.7 1960.37  5149.7 1959.36  5179.7 1959.63  5189.7 1960.63
  5237.7 1958.68  5237.9 1958.18  5241.4 1958.18  5241.7 1958.68  5245.0 1959.45
#Mann=5,-1,0
  4777.7    0.07       0  4800.5    0.16       0  5000.9    0.07       0
  5237.7    0.07       0  5241.7    0.07       0
Bank Sta=5237.7,5241.7
Exp/Cntr=0.3,0.1

Type RM Length L Ch R = 1,406,84,84,84
BEGIN DESCRIPTION:
Elm 99 4013
END DESCRIPTION:
XS GIS Cut Line= 3
      1549666.15      6774913.03      1549474.09      6775008.53
      1549431.14      6775044.00
#Sta/Elev= 30
  4785.5 1962.10  4798.0 1961.96  4805.7 1962.15  4820.3 1962.15  4828.1 1961.57
  4833.7 1960.90  4842.6 1960.61  4856.1 1960.86  4865.0 1960.83  4872.9 1960.20
  4878.5 1960.95  4887.3 1961.75  4900.9 1961.64  4917.7 1961.18  4923.3 1961.28
  4940.1 1960.41  4945.7 1960.68  4954.3 1959.67  4962.5 1959.21  4968.1 1959.36
  4974.6 1958.96  4974.9 1958.46  4978.4 1958.46  4978.6 1958.96  4984.9 1959.10
  5034.8 1959.26  5041.3 1958.98  5044.4 1958.99  5049.2 1959.00  5055.7 1959.74
#Mann=4,-1,0
  4785.5    0.16       0  4974.6    0.07       0  4978.6    0.16       0
  5044.4    0.07       0
Bank Sta=4974.6,4978.6
Exp/Cntr=0.3,0.1

Type RM Length L Ch R = 1,322,131,131,131
BEGIN DESCRIPTION:
Elm 99 4014
END DESCRIPTION:
XS GIS Cut Line= 3
      1549677.95      6774880.09      1549498.96      6774940.47
      1549335.73      6774902.88
#Sta/Elev= 30
  4811.1 1962.23  4828.0 1962.20  4845.9 1963.06  4851.3 1961.94  4877.5 1961.54
  4882.8 1961.71  4914.3 1961.88  4919.8 1961.63  4945.7 1961.16  4951.4 1960.92
  4962.0 1959.87  4971.9 1959.32  4977.2 1959.37  4983.1 1959.02  5024.6 1959.03
  5031.5 1959.25  5036.6 1958.83  5065.6 1959.17  5072.3 1958.83  5072.6 1958.33
  5076.1 1958.33  5076.3 1958.83  5079.4 1959.43  5086.2 1958.85  5123.3 1959.00
  5127.4 1959.02  5137.5 1960.55  5147.7 1963.31  5158.3 1964.83  5167.5 1966.97
#Mann=6,-1,0
  4811.1    0.07       0  4828.0    0.16       0  5072.3    0.07       0
  5076.3    0.16       0  5123.3    0.07       0  5158.3    0.16       0
Bank Sta=5072.3,5076.3
Exp/Cntr=0.3,0.1

Type RM Length L Ch R = 1,191,121,121,121
BEGIN DESCRIPTION:
Elm 99 4012
END DESCRIPTION:
XS GIS Cut Line= 3
      1549678.00      6774836.55      1549504.49      6774810.17
      1549384.39      6774824.01
#Sta/Elev= 30
  4824.5 1961.19  4837.6 1961.26  4850.5 1960.58  4867.1 1960.58  4878.1 1960.36
  4888.2 1960.52  4908.5 1959.52  4914.1 1959.46  4919.1 1959.97  4938.8 1959.73
  4948.9 1959.37  4959.0 1959.55  4969.1 1960.13  4977.7 1960.27  4982.7 1960.89
  4997.2 1959.76  5002.3 1959.76  5009.6 1959.07  5027.7 1958.84  5028.0 1958.34
  5031.5 1958.34  5031.7 1958.84  5054.5 1959.03  5080.0 1959.08  5090.1 1959.38
  5100.2 1962.00  5108.6 1963.89  5113.7 1962.74  5118.1 1964.35  5120.9 1964.35
#Mann=5,-1,0
  4824.5    0.07       0  4867.1    0.16       0  5027.7    0.07       0
  5031.7    0.16       0  5054.5    0.07       0
Bank Sta=5027.7,5031.7
Exp/Cntr=0.3,0.1

Type RM Length L Ch R = 1,70,0,0,0
BEGIN DESCRIPTION:
Elm 99 4011
END DESCRIPTION:
XS GIS Cut Line= 3
      1549596.19      6774716.52      1549501.71      6774689.36
      1549409.47      6774742.59
#Sta/Elev= 30
  4901.7 1961.31  4911.3 1961.30  4918.5 1961.54  4923.7 1961.52  4934.2 1962.01
  4944.6 1961.95  4950.2 1961.65  4955.4 1961.86  4965.4 1961.13  4975.8 1960.65
  4989.1 1961.23  4995.7 1962.94  5000.0 1962.94  5004.6 1963.69  5010.4 1963.92
  5019.3 1961.83  5026.2 1961.49  5032.0 1961.39  5042.0 1961.50  5047.7 1960.12
  5051.9 1959.79  5052.2 1959.29  5055.7 1959.29  5055.9 1959.79  5063.5 1960.17
  5069.3 1961.18  5077.0 1961.08  5085.1 1960.60  5090.8 1960.81  5106.5 1960.44
#Mann=4,-1,0
  4901.7    0.07       0  4918.5    0.16       0  5051.9    0.07       0
  5055.9    0.16       0
Bank Sta=5051.9,5055.9
Exp/Cntr=0.3,0.1

Chan Stop Cuts=-1