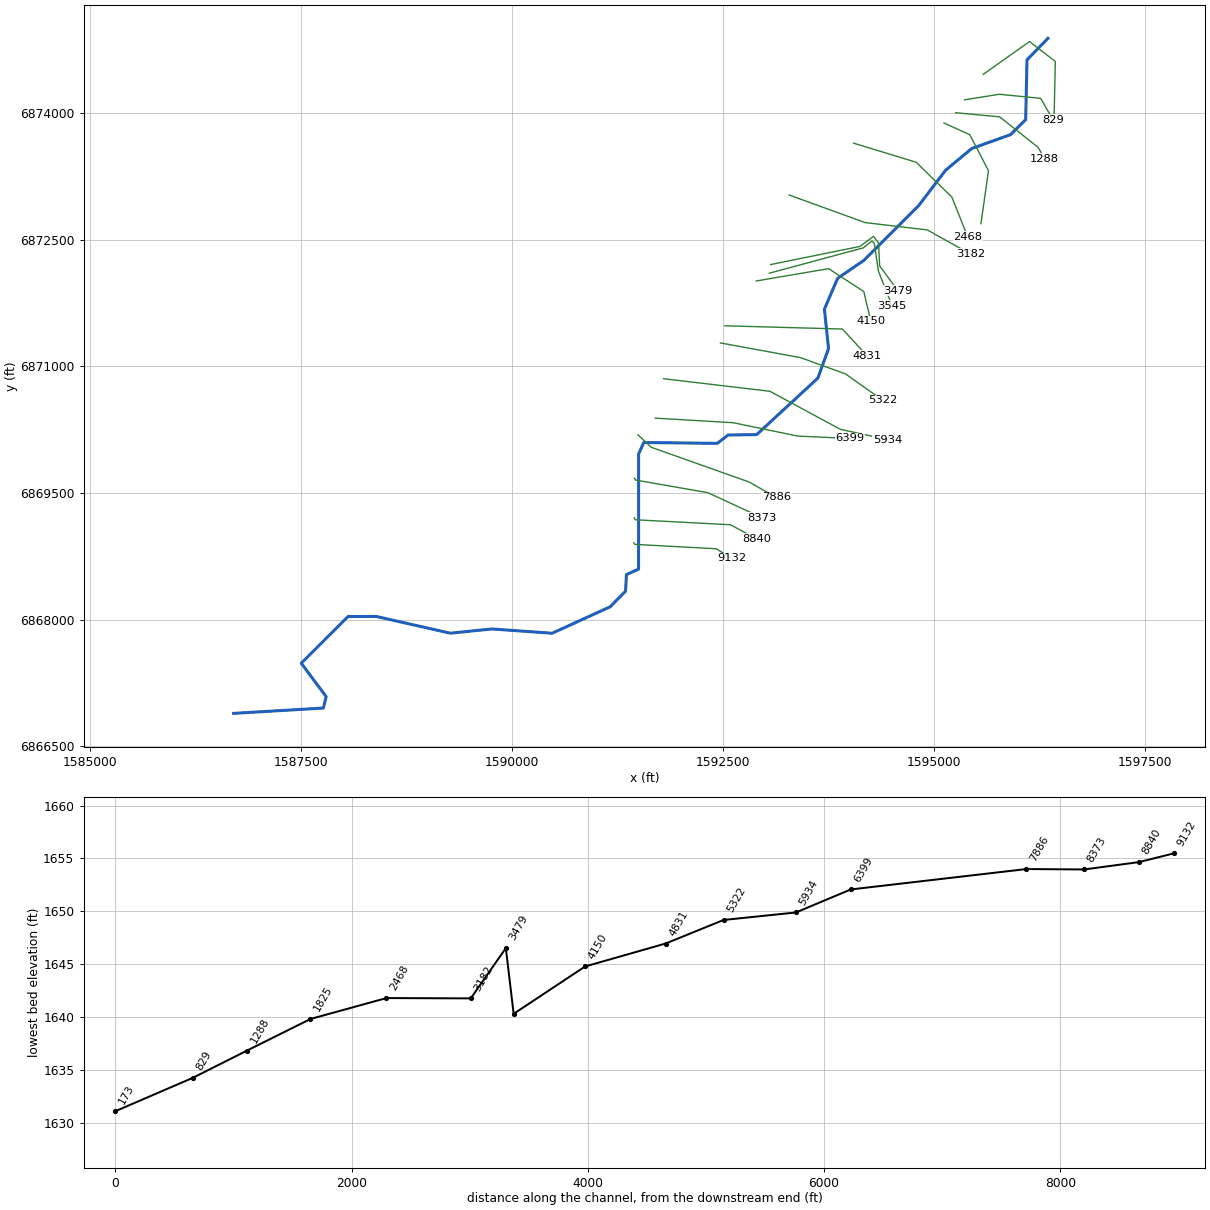
--- Elm Cr to Cedar Cr Overflow.prj (project) ---

Proj Title=Elm Cr to Cedar Cr Overflow Base Level Engineering
Current Plan=p01
Default Exp/Contr=0.3,0.1
English Units
Geom File=g01
Flow File=f01
Plan File=p01
Y Axis Title=Elevation
X Axis Title(PF)=Main Channel Distance
X Axis Title(XS)=Station
BEGIN DESCRIPTION:
Elm Cr to Cedar Cr Overflow
END DESCRIPTION:
DSS Export Rating Curves= 0
DSS Export Rating Curve Sorted= 0
DSS Export Volume Flow Curves= 0
DXF OffsetX= 0
DXF OffsetY= 0
DXF ScaleX= 1
DXF ScaleY= 10

--- Elm Cr to Cedar Cr Overflow.p01 (plan) ---

Plan Title=Multiple Run
Short Identifier=Multiple
Geom File=g01
Flow File=f01
Subcritical Flow
K Sum by GR= 0
Std Step Tol= 0.01
Critical Tol= 0.01
Num of Std Step Trials= 20
Max Error Tol= 0.3
Flow Tol Ratio= 0.001
Split Flow NTrial= 30
Split Flow Tol= 0.02
Split Flow Ratio= 0.02
Log Output Level= 0
Friction Slope Method= 1
Unsteady Friction Slope Method= 2
Unsteady Bridges Friction Slope Method= 1
Parabolic Critical Depth
Global Vel Dist=  1 , 1 , 1
Global Log Level= 0
CheckData=True
Encroach Param= -1, 0, 0, 0
BEGIN DESCRIPTION:
Multiple Run
END DESCRIPTION:

--- Elm Cr to Cedar Cr Overflow.f01 (steady flow) ---

Flow Title=Multiple
Program Version=4.10
Number of Profiles= 7
Profile Names=10-year,25-year,50-year,1pct_min,100-year,1pct_plu,500-year
River Rch & RM=Elm Cr to Cedar,Reach-1         ,9132
     301     411     500     376     603     830     889
Boundary for River Rch & Prof#=Elm Cr to Cedar,Reach-1         , 1
Up Type= 0
Dn Type= 3
Dn Slope=0.005
Boundary for River Rch & Prof#=Elm Cr to Cedar,Reach-1         , 2
Up Type= 0
Dn Type= 3
Dn Slope=0.005
Boundary for River Rch & Prof#=Elm Cr to Cedar,Reach-1         , 3
Up Type= 0
Dn Type= 3
Dn Slope=0.005
Boundary for River Rch & Prof#=Elm Cr to Cedar,Reach-1         , 4
Up Type= 0
Dn Type= 3
Dn Slope=0.005
Boundary for River Rch & Prof#=Elm Cr to Cedar,Reach-1         , 5
Up Type= 0
Dn Type= 3
Dn Slope=0.005
Boundary for River Rch & Prof#=Elm Cr to Cedar,Reach-1         , 6
Up Type= 0
Dn Type= 3
Dn Slope=0.005
Boundary for River Rch & Prof#=Elm Cr to Cedar,Reach-1         , 7
Up Type= 0
Dn Type= 3
Dn Slope=0.005
DSS Import GetInterval= 0
DSS Import GetPeak= 0
DSS Import FillOption= 0

--- Elm Cr to Cedar Cr Overflow.g01 (geometry) ---

Geom Title=Existing Conditions

River Reach=Elm Cr to Cedar ,Reach-1
Reach XY= 30
      1586705.00      6866888.00      1587768.75      6866951.20
      1587801.53      6867086.50      1587506.69      6867482.36
      1588060.44      6868035.83      1588394.50      6868036.78
      1589273.27      6867838.21      1589765.19      6867888.45
      1590480.08      6867837.80      1591168.21      6868151.62
      1591349.54      6868335.55      1591360.04      6868532.92
      1591503.87      6868597.41      1591504.79      6869963.09
      1591565.61      6870098.06      1592436.78      6870088.09
      1592564.59      6870186.79      1592903.54      6870191.54
      1593628.83      6870861.13      1593755.14      6871210.85
      1593706.38      6871678.34      1593863.13      6872044.07
      1594171.71      6872254.64      1594825.39      6872907.84
      1595141.79      6873324.37      1595452.70      6873582.17
      1595911.06      6873746.14      1596091.63      6873924.68
      1596107.17      6874632.57      1596355.00      6874888.00

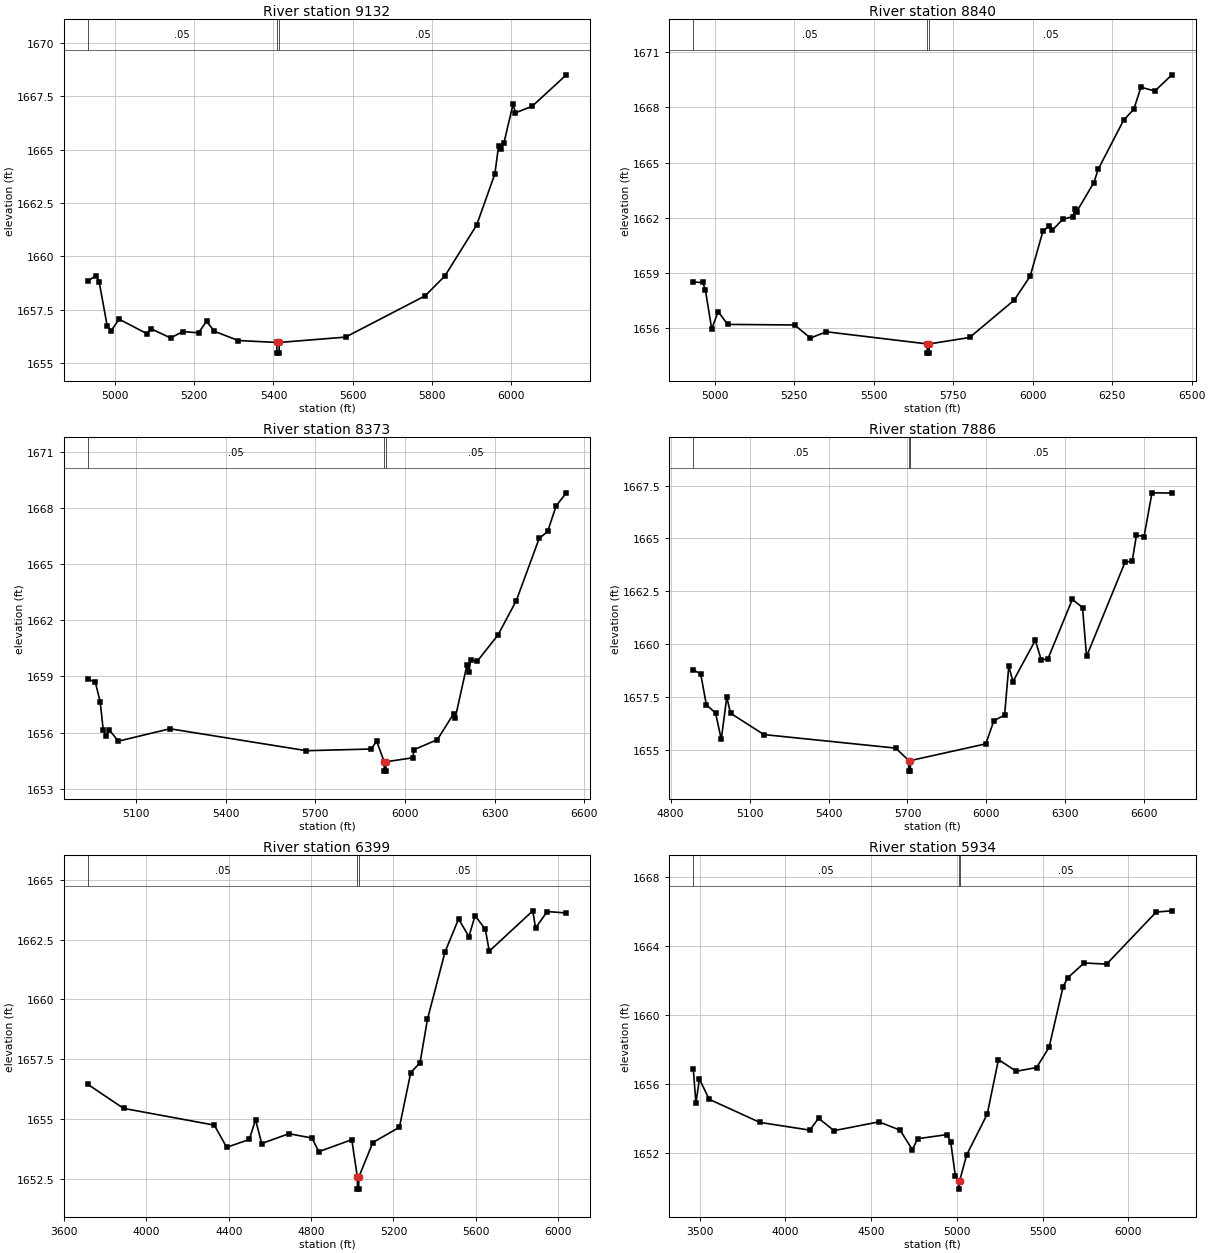
Type RM Length L Ch R = 1,9132,292,292,292
BEGIN DESCRIPTION:
Mapping XS 8b5404c9
END DESCRIPTION:
XS GIS Cut Line= 4
      1591446.53      6868910.03      1591458.71      6868890.90
      1592425.72      6868838.82      1592608.01      6868724.24
#Sta/Elev= 30
  4931.9 1658.85  4953.3 1659.10  4960.9 1658.79  4980.9 1656.75  4990.9 1656.52
  5011.0 1657.06  5081.1 1656.38  5091.1 1656.61  5141.1 1656.18  5171.2 1656.48
  5211.2 1656.42  5231.3 1656.96  5251.3 1656.49  5311.4 1656.06  5408.4 1655.97
  5408.9 1655.47  5414.2 1655.47  5414.7 1655.97  5581.8 1656.22  5782.1 1658.15
  5832.1 1659.08  5912.3 1661.47  5958.1 1663.86  5967.5 1665.17  5973.4 1665.02
  5981.2 1665.33  6004.0 1667.13  6009.9 1666.72  6052.3 1667.03  6138.3 1668.50
#Mann=3,-1,0
  4931.9    0.05       0  5408.4    0.03       0  5414.7    0.05       0
Bank Sta=5408.4,5414.7
Exp/Cntr=0.3,0.1

Type RM Length L Ch R = 1,8840,467,467,467
BEGIN DESCRIPTION:
Mapping XS 1abe3e17
END DESCRIPTION:
XS GIS Cut Line= 4
      1591453.06      6869206.89      1591463.48      6869182.57
      1592591.95      6869123.54      1592899.21      6868958.63
#Sta/Elev= 30
  4932.7 1658.51  4962.4 1658.49  4970.7 1658.09  4990.7 1655.96  5010.8 1656.91
  5040.8 1656.21  5251.1 1656.18  5301.2 1655.47  5351.2 1655.81  5668.5 1655.15
  5669.0 1654.65  5674.3 1654.65  5674.8 1655.15  5801.8 1655.50  5942.0 1657.53
  5992.1 1658.83  6032.1 1661.26  6052.2 1661.58  6062.2 1661.33  6094.3 1661.92
  6126.7 1662.07  6132.5 1662.49  6138.2 1662.33  6192.6 1663.92  6206.1 1664.64
  6285.9 1667.30  6318.4 1667.91  6340.4 1669.10  6384.2 1668.89  6437.9 1669.77
#Mann=3,-1,0
  4932.7    0.05       0  5668.5    0.03       0  5674.8    0.05       0
Bank Sta=5668.5,5674.8
Exp/Cntr=0.3,0.1

Type RM Length L Ch R = 1,8373,487,487,487
BEGIN DESCRIPTION:
Mapping XS 57f5cb2a
END DESCRIPTION:
XS GIS Cut Line= 4
      1591454.78      6869673.91      1591468.69      6869653.05
      1592324.59      6869503.75      1592966.91      6869206.89
#Sta/Elev= 30
  4938.5 1658.86  4963.6 1658.71  4980.1 1657.66  4990.3 1656.17  5000.4 1655.81
  5010.6 1656.15  5041.0 1655.55  5213.6 1656.21  5670.4 1655.04  5887.9 1655.13
  5905.1 1655.56  5930.4 1654.45  5930.9 1653.95  5936.2 1653.95  5936.7 1654.45
  6025.3 1654.66  6031.1 1655.10  6108.3 1655.63  6162.9 1657.01  6168.4 1656.80
  6207.4 1659.60  6214.2 1659.25  6219.7 1659.86  6242.7 1659.83  6311.5 1661.22
  6372.6 1663.05  6449.1 1666.37  6477.5 1666.74  6506.0 1668.11  6540.0 1668.80
#Mann=3,-1,0
  4938.5    0.05       0  5930.4    0.03       0  5936.7    0.05       0
Bank Sta=5930.4,5936.7
Exp/Cntr=0.3,0.1

Type RM Length L Ch R = 1,7886,1487,1487,1487
BEGIN DESCRIPTION:
Mapping XS 854fc130
END DESCRIPTION:
XS GIS Cut Line= 4
      1591496.46      6870189.51      1591652.72      6870041.94
      1592812.44      6869630.48      1593137.13      6869446.44
#Sta/Elev= 30
  4886.2 1658.78  4914.4 1658.59  4935.9 1657.13  4971.0 1656.74  4992.5 1655.49
  5013.5 1657.49  5027.7 1656.73  5154.5 1655.72  5655.3 1655.08  5705.2 1654.49
  5705.7 1653.99  5711.0 1653.99  5711.5 1654.49  5997.7 1655.28  6028.5 1656.38
  6069.1 1656.64  6085.0 1658.95  6101.0 1658.23  6185.8 1660.18  6208.4 1659.25
  6234.0 1659.31  6326.6 1662.12  6365.2 1661.73  6380.6 1659.42  6526.8 1663.88
  6554.2 1663.93  6570.1 1665.16  6599.0 1665.09  6629.2 1667.16  6704.9 1667.15
#Mann=3,-1,0
  4886.2    0.05       0  5705.2    0.03       0  5711.5    0.05       0
Bank Sta=5705.2,5711.5
Exp/Cntr=0.3,0.1

Type RM Length L Ch R = 1,6399,465,465,465
BEGIN DESCRIPTION:
Mapping XS 8925c715
END DESCRIPTION:
XS GIS Cut Line= 4
      1591701.15      6870386.99      1592625.59      6870332.74
      1593389.48      6870174.32      1594007.97      6870146.11
#Sta/Elev= 30
  3714.7 1656.45  3888.8 1655.44  4329.6 1654.74  4389.7 1653.81  4499.9 1654.14
  4529.9 1654.97  4560.0 1653.97  4692.5 1654.38  4803.5 1654.20  4837.9 1653.63
  4997.6 1654.13  5024.8 1652.56  5025.3 1652.06  5031.1 1652.06  5031.6 1652.56
  5099.7 1654.01  5228.9 1654.65  5284.1 1656.94  5329.2 1657.35  5365.2 1659.17
  5450.6 1661.99  5516.5 1663.37  5566.5 1662.63  5596.6 1663.51  5646.6 1662.93
  5665.5 1662.02  5876.9 1663.71  5890.3 1662.99  5946.9 1663.68  6040.0 1663.62
#Mann=3,-1,0
  3714.7    0.05       0  5024.8    0.05       0  5031.6    0.05       0
Bank Sta=5024.8,5031.6
Exp/Cntr=0.3,0.1

Type RM Length L Ch R = 1,5934,612,612,612
BEGIN DESCRIPTION:
Mapping XS 32e8229d
END DESCRIPTION:
XS GIS Cut Line= 4
      1591799.79      6870854.21      1593060.92      6870705.14
      1593894.25      6870254.62      1594455.00      6870132.60
#Sta/Elev= 30
  3462.8 1656.89  3478.1 1654.87  3498.3 1656.28  3556.0 1655.10  3850.7 1653.76
  4142.7 1653.31  4193.1 1654.00  4283.7 1653.28  4545.5 1653.79  4668.5 1653.31
  4740.1 1652.18  4771.5 1652.81  4941.9 1653.05  4963.8 1652.63  4991.3 1650.64
  5009.8 1650.38  5010.3 1649.88  5016.6 1650.38  5057.0 1651.87  5176.9 1654.24
  5242.5 1657.41  5346.3 1656.73  5464.9 1656.95  5537.5 1658.12  5619.4 1661.65
  5646.9 1662.17  5742.2 1663.03  5872.9 1662.96  6162.4 1665.99  6253.9 1666.06
#Mann=3,-1,0
  3462.8    0.05       0  5009.8    0.05       0  5016.6    0.05       0
Bank Sta=5009.8,5016.6
Exp/Cntr=0.3,0.1

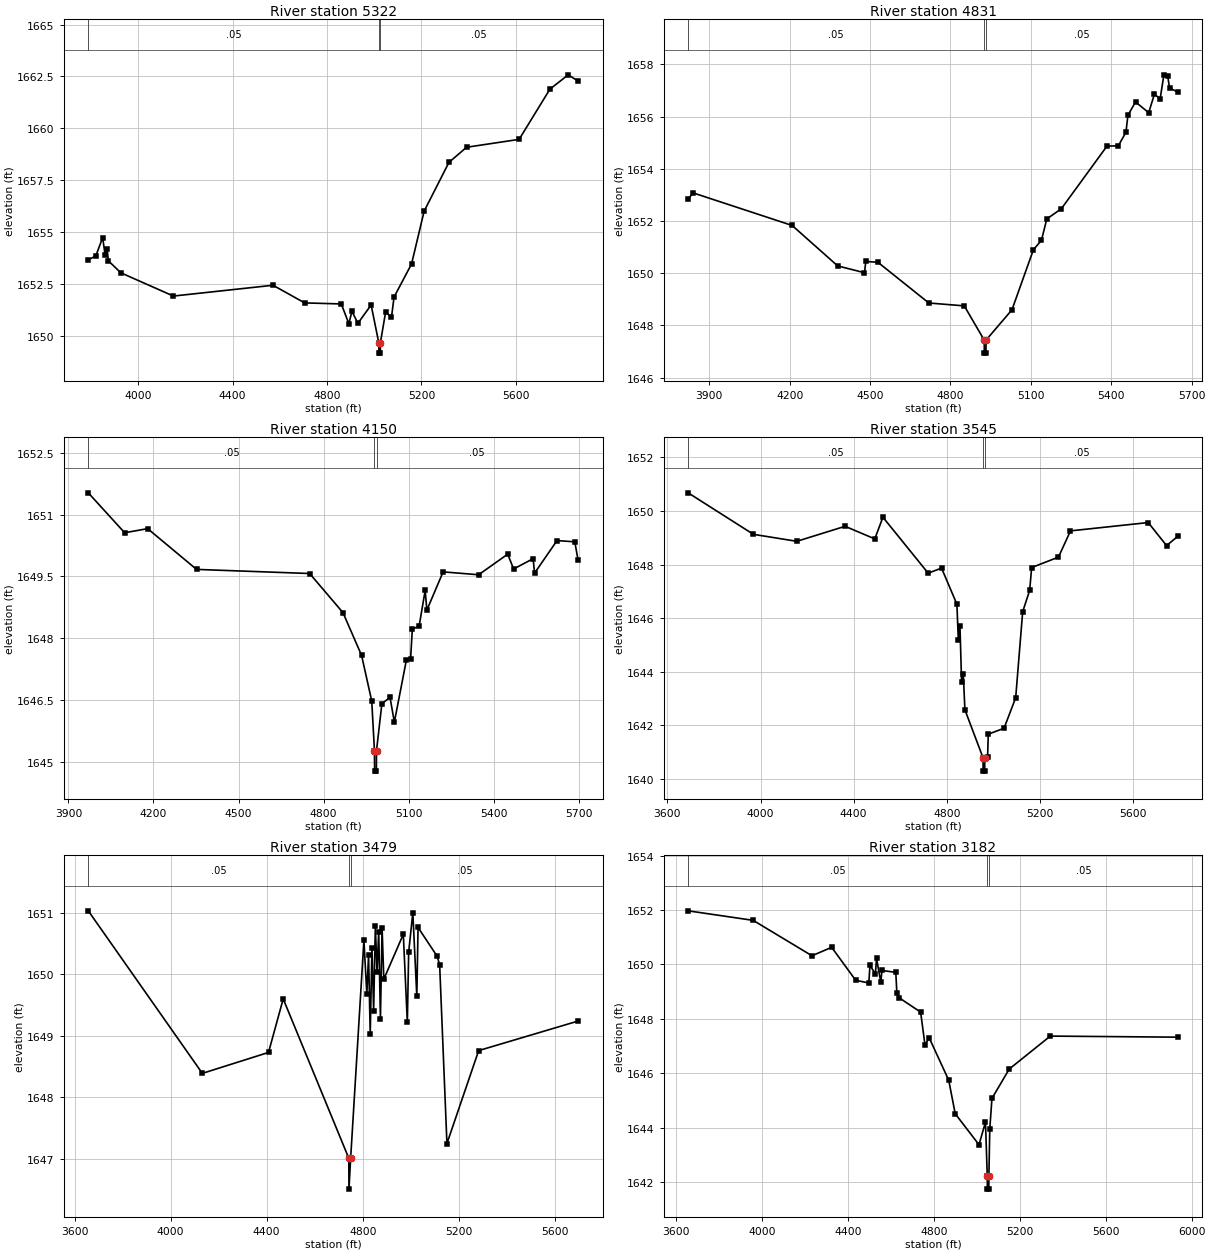
Type RM Length L Ch R = 1,5322,491,491,491
BEGIN DESCRIPTION:
Mapping XS 4d25606f
END DESCRIPTION:
XS GIS Cut Line= 4
      1592474.95      6871278.06      1593425.50      6871103.57
      1593956.75      6870910.87      1594401.03      6870596.50
#Sta/Elev= 30
  3788.2 1653.67  3820.0 1653.85  3849.2 1654.74  3859.4 1653.90  3868.1 1654.21
  3873.1 1653.62  3926.2 1653.04  4148.9 1651.92  4571.1 1652.44  4705.4 1651.59
  4860.5 1651.54  4892.4 1650.59  4905.6 1651.18  4930.9 1650.61  4986.9 1651.49
  5019.3 1649.67  5019.8 1649.17  5025.7 1649.17  5026.2 1649.67  5048.1 1651.14
  5073.2 1650.90  5084.0 1651.87  5158.3 1653.47  5211.5 1656.01  5316.6 1658.36
  5391.3 1659.09  5614.1 1659.47  5744.6 1661.89  5822.1 1662.58  5864.0 1662.28
#Mann=3,-1,0
  3788.2    0.05       0  5019.3    0.05       0  5026.2    0.05       0
Bank Sta=5019.3,5026.2
Exp/Cntr=0.3,0.1

Type RM Length L Ch R = 1,4831,681,681,681
BEGIN DESCRIPTION:
Mapping XS 2f46da81
END DESCRIPTION:
XS GIS Cut Line= 3
      1592527.09      6871481.18      1593919.43      6871442.98
      1594214.58      6871123.52
#Sta/Elev= 30
  3821.1 1652.83  3839.0 1653.08  4209.2 1651.83  4379.2 1650.28  4479.1 1650.02
  4484.1 1650.45  4529.3 1650.42  4719.3 1648.86  4851.5 1648.75  4925.9 1647.44
  4926.4 1646.94  4932.4 1646.94  4932.9 1647.44  5029.5 1648.60  5109.5 1650.90
  5139.5 1651.26  5159.5 1652.08  5213.7 1652.47  5384.1 1654.87  5426.4 1654.88
  5454.8 1655.40  5462.2 1656.05  5490.5 1656.56  5539.8 1656.15  5561.1 1656.86
  5582.4 1656.68  5596.5 1657.60  5610.7 1657.56  5617.5 1657.09  5648.9 1656.94
#Mann=3,-1,0
  3821.1    0.05       0  4925.9    0.05       0  4932.9    0.05       0
Bank Sta=4925.9,4932.9
Exp/Cntr=0.3,0.1

Type RM Length L Ch R = 1,4150,605,605,605
BEGIN DESCRIPTION:
Mapping XS b651864b
END DESCRIPTION:
XS GIS Cut Line= 4
      1592898.56      6872012.42      1593756.23      6872158.26
      1594172.90      6871887.43      1594256.23      6871536.73
#Sta/Elev= 30
  3970.2 1651.53  4098.5 1650.56  4179.6 1650.66  4352.0 1649.67  4750.9 1649.57
  4868.4 1648.62  4934.1 1647.58  4969.9 1646.47  4979.4 1645.27  4979.9 1644.77
  4986.2 1644.77  4986.7 1645.27  5005.7 1646.41  5034.4 1646.56  5049.6 1645.96
  5091.8 1647.46  5106.9 1647.50  5113.0 1648.22  5136.9 1648.29  5158.3 1649.16
  5164.2 1648.68  5221.6 1649.61  5346.8 1649.54  5449.4 1650.04  5470.2 1649.68
  5538.9 1649.93  5544.1 1649.58  5623.3 1650.37  5686.0 1650.34  5697.6 1649.89
#Mann=3,-1,0
  3970.2    0.05       0  4979.4    0.05       0  4986.7    0.05       0
Bank Sta=4979.4,4986.7
Exp/Cntr=0.3,0.1

Type RM Length L Ch R = 1,3545,66,66,66
BEGIN DESCRIPTION:
Mapping XS dc8acded
END DESCRIPTION:
XS GIS Cut Line= 6
      1593054.39      6872104.87      1594165.52      6872404.36
      1594269.69      6872486.82      1594297.90      6872458.61
      1594345.64      6872130.92      1594508.13      6871717.94
#Sta/Elev= 30
  3689.2 1650.68  3969.5 1649.13  4155.9 1648.87  4363.0 1649.43  4490.7 1648.96
  4525.5 1649.77  4719.9 1647.68  4777.3 1647.87  4843.2 1646.52  4849.3 1645.19
  4856.3 1645.71  4863.4 1643.60  4870.5 1643.92  4877.6 1642.58  4955.3 1640.79
  4955.8 1640.29  4962.4 1640.29  4962.9 1640.79  4975.0 1640.83  4977.9 1641.67
  5045.6 1641.89  5095.6 1643.03  5125.6 1646.24  5155.7 1647.04  5164.1 1647.89
  5279.3 1648.28  5330.9 1649.26  5664.7 1649.57  5743.3 1648.71  5792.3 1649.06
#Mann=3,-1,0
  3689.2    0.05       0  4955.3    0.05       0  4962.9    0.05       0
Bank Sta=4955.3,4962.9
Exp/Cntr=0.3,0.1

Type RM Length L Ch R = 1,3479,297,297,297
BEGIN DESCRIPTION:
Mapping XS 76d6dc06
END DESCRIPTION:
XS GIS Cut Line= 6
      1593069.64      6872206.88      1594126.46      6872421.72
      1594289.22      6872541.07      1594347.81      6872460.78
      1594360.83      6872191.68      1594577.61      6871895.85
#Sta/Elev= 30
  3657.2 1651.03  4132.1 1648.39  4407.6 1648.73  4468.8 1649.60  4742.0 1647.01
  4742.5 1646.51  4749.6 1647.01  4804.8 1650.55  4817.0 1649.68  4824.2 1650.31
  4831.1 1649.03  4838.3 1650.43  4845.3 1649.41  4852.4 1650.78  4859.4 1650.04
  4866.4 1650.69  4873.6 1649.28  4880.5 1650.75  4887.7 1649.92  4968.9 1650.65
  4985.6 1649.22  4991.2 1650.36  5008.5 1651.00  5025.1 1649.64  5030.2 1650.76
  5110.1 1650.29  5120.2 1650.15  5150.5 1647.25  5282.6 1648.76  5696.6 1649.24
#Mann=3,-1,0
  3657.2    0.05       0  4742.0    0.05       0  4749.6    0.05       0
Bank Sta=4742,4749.6
Exp/Cntr=0.3,0.1

Type RM Length L Ch R = 1,3182,714,714,714
BEGIN DESCRIPTION:
Mapping XS a8cc4338
END DESCRIPTION:
XS GIS Cut Line= 4
      1593290.05      6873030.67      1594189.39      6872704.27
      1594925.50      6872617.46      1595435.65      6872332.89
#Sta/Elev= 30
  3654.7 1651.97  3957.8 1651.62  4231.6 1650.32  4323.4 1650.63  4435.3 1649.42
  4496.5 1649.32  4501.8 1649.97  4527.1 1649.65  4532.4 1650.22  4552.4 1649.35
  4557.7 1649.78  4622.2 1649.71  4627.2 1648.95  4637.2 1648.78  4737.9 1648.25
  4758.1 1647.05  4778.2 1647.30  4868.8 1645.75  4899.0 1644.52  5009.8 1643.38
  5040.0 1644.21  5048.3 1642.25  5048.8 1641.75  5055.5 1641.75  5056.0 1642.25
  5060.1 1643.96  5070.2 1645.08  5150.8 1646.16  5342.1 1647.37  5936.8 1647.33
#Mann=3,-1,0
  3654.7    0.05       0  5048.3    0.05       0  5056.0    0.05       0
Bank Sta=5048.3,5056
Exp/Cntr=0.3,0.1

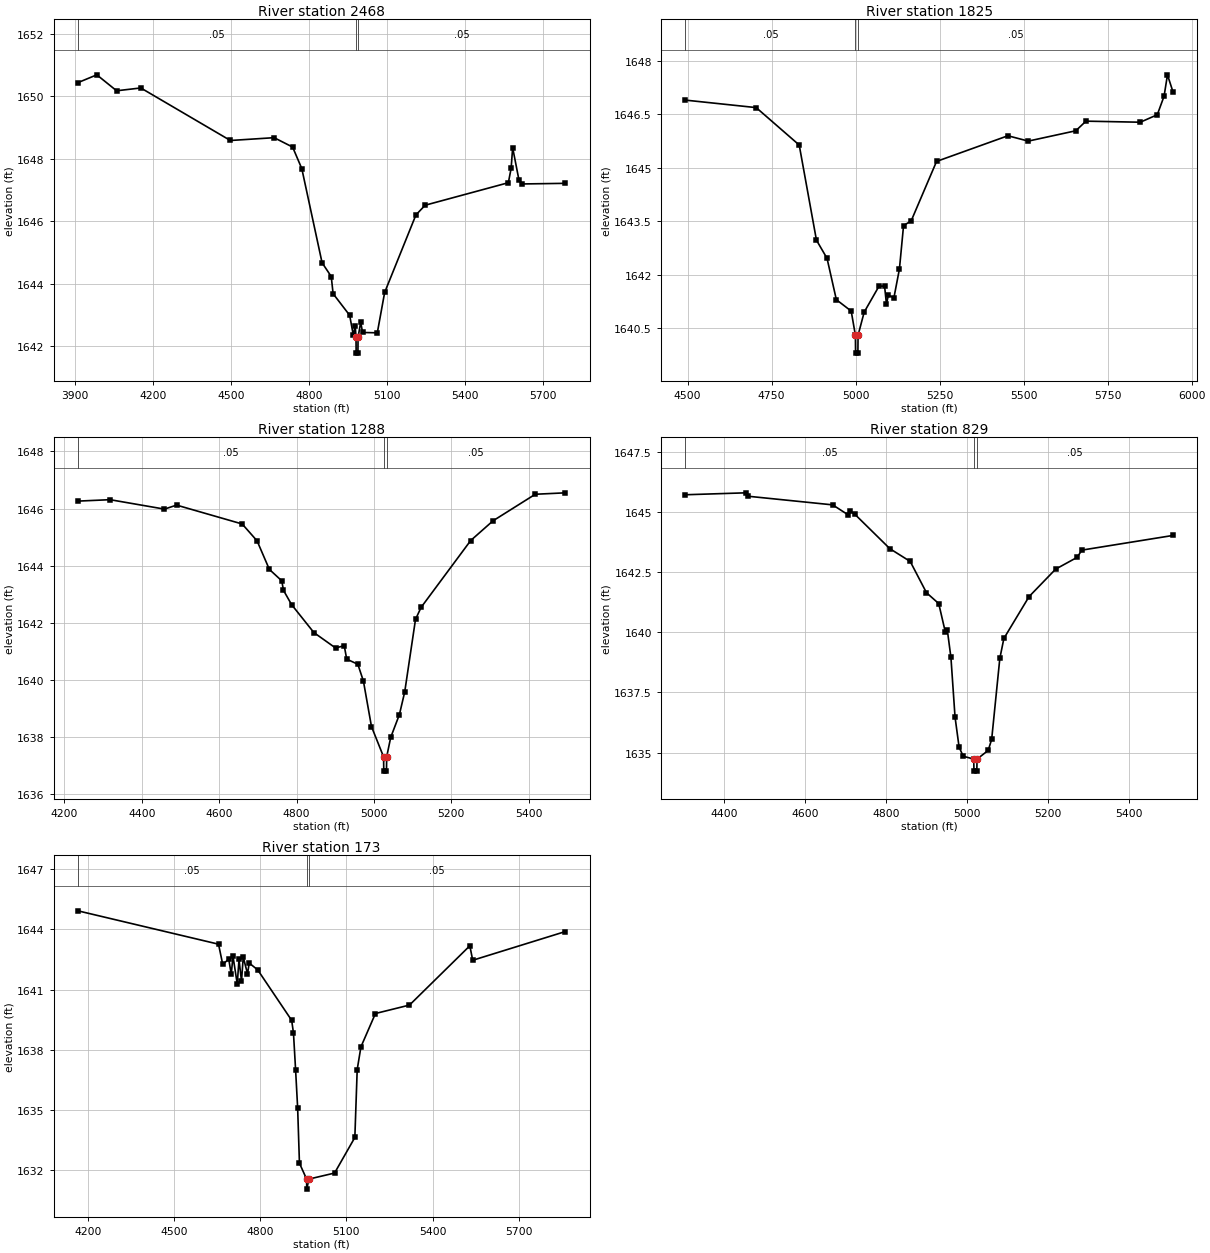
Type RM Length L Ch R = 1,2468,643,643,643
BEGIN DESCRIPTION:
Mapping XS f3743bd0
END DESCRIPTION:
XS GIS Cut Line= 4
      1594053.95      6873645.25      1594793.56      6873419.55
      1595217.17      6873006.35      1595404.66      6872534.15
#Sta/Elev= 30
  3912.9 1650.43  3985.5 1650.68  4061.6 1650.17  4154.5 1650.26  4498.7 1648.58
  4666.8 1648.67  4737.8 1648.37  4773.1 1647.68  4851.0 1644.67  4886.2 1644.23
  4893.4 1643.68  4957.0 1642.99  4971.1 1642.35  4978.3 1642.66  4981.4 1642.28
  4981.9 1641.78  4988.7 1641.78  4989.2 1642.28  4999.4 1642.77  5006.6 1642.44
  5063.2 1642.43  5091.4 1643.72  5211.6 1646.20  5247.0 1646.51  5566.7 1647.23
  5577.4 1647.69  5583.2 1648.35  5607.6 1647.31  5620.5 1647.19  5786.0 1647.21
#Mann=3,-1,0
  3912.9    0.05       0  4981.4    0.05       0  4989.2    0.05       0
Bank Sta=4981.4,4989.2
Exp/Cntr=0.3,0.1

Type RM Length L Ch R = 1,1825,537,537,537
BEGIN DESCRIPTION:
Mapping XS aac3ab6e
END DESCRIPTION:
XS GIS Cut Line= 4
      1595123.44      6873884.81      1595428.98      6873745.94
      1595651.20      6873318.85      1595561.10      6872691.64
#Sta/Elev= 30
  4493.8 1646.90  4704.2 1646.69  4832.2 1645.64  4883.5 1642.97  4915.0 1642.46
  4942.7 1641.30  4986.9 1640.98  4999.4 1640.30  4999.9 1639.80  5006.8 1639.80
  5007.3 1640.30  5025.5 1640.95  5069.7 1641.68  5086.2 1641.68  5091.8 1641.18
  5097.6 1641.43  5113.9 1641.35  5130.4 1642.16  5142.7 1643.38  5165.3 1643.51
  5240.9 1645.18  5453.2 1645.90  5513.8 1645.75  5655.2 1646.04  5685.5 1646.31
  5847.2 1646.28  5897.7 1646.49  5917.9 1647.01  5928.0 1647.61  5944.5 1647.13
#Mann=3,-1,0
  4493.8    0.05       0  4999.4   0.035       0  5007.3    0.05       0
Bank Sta=4999.4,5007.3
Exp/Cntr=0.3,0.1

Type RM Length L Ch R = 1,1288,459,459,459
BEGIN DESCRIPTION:
Mapping XS 831e020b
END DESCRIPTION:
XS GIS Cut Line= 4
      1595262.35      6874006.35      1595783.14      6873957.74
      1596238.00      6873596.63      1596317.34      6873462.11
#Sta/Elev= 30
  4234.8 1646.26  4317.8 1646.31  4458.4 1645.98  4489.8 1646.12  4659.3 1645.46
  4697.8 1644.87  4729.6 1643.87  4761.7 1643.47  4766.0 1643.14  4786.9 1642.64
  4844.6 1641.66  4900.7 1641.12  4923.1 1641.20  4929.5 1640.73  4958.3 1640.55
  4972.7 1639.96  4993.5 1638.37  5024.8 1637.31  5025.3 1636.81  5032.3 1636.81
  5032.8 1637.31  5043.2 1637.99  5065.7 1638.79  5079.4 1639.58  5107.3 1642.12
  5121.7 1642.54  5249.9 1644.88  5307.6 1645.57  5416.9 1646.50  5494.8 1646.55
#Mann=3,-1,0
  4234.8    0.05       0  5024.8   0.035       0  5032.8    0.05       0
Bank Sta=5024.8,5032.8
Exp/Cntr=0.3,0.1

Type RM Length L Ch R = 1,829,656,656,656
BEGIN DESCRIPTION:
Mapping XS 1e3c15c5
END DESCRIPTION:
XS GIS Cut Line= 4
      1595366.49      6874159.13      1595779.67      6874225.10
      1596269.25      6874176.49      1596415.07      6873923.05
#Sta/Elev= 30
  4305.3 1645.71  4453.7 1645.79  4458.7 1645.65  4668.4 1645.29  4707.1 1644.87
  4712.2 1645.03  4723.7 1644.89  4809.5 1643.47  4859.7 1642.94  4899.9 1641.64
  4930.1 1641.19  4946.3 1640.01  4951.3 1640.09  4960.2 1638.95  4970.3 1636.48
  4980.3 1635.23  4990.4 1634.85  5016.5 1634.73  5017.0 1634.23  5024.1 1634.23
  5024.6 1634.73  5052.1 1635.09  5060.7 1635.55  5080.8 1638.91  5090.8 1639.74
  5153.0 1641.48  5218.5 1642.62  5271.6 1643.11  5283.2 1643.41  5508.1 1644.02
#Mann=3,-1,0
  4305.3    0.05       0  5016.5   0.035       0  5024.6    0.05       0
Bank Sta=5016.5,5024.6
Exp/Cntr=0.3,0.1

Type RM Length L Ch R = 1,173,0,0,0
BEGIN DESCRIPTION:
Elm Cr to Cedar Cr Overflow 1.0
END DESCRIPTION:
XS GIS Cut Line= 4
      1595588.72      6874461.23      1596137.31      6874850.10
      1596442.87      6874613.99      1596428.98      6873975.13
#Sta/Elev= 30
  4165.1 1644.92  4654.7 1643.26  4669.4 1642.25  4690.3 1642.52  4699.0 1641.76
  4705.1 1642.66  4719.9 1641.28  4726.0 1642.50  4734.7 1641.42  4740.8 1642.62
  4755.6 1641.79  4761.7 1642.32  4791.2 1641.98  4909.4 1639.47  4915.7 1638.84
  4923.1 1637.00  4930.2 1635.12  4936.5 1632.36  4961.4 1631.57  4961.9 1631.07
  4969.5 1631.57  5058.8 1631.87  5129.4 1633.64  5137.6 1637.02  5150.6 1638.15
  5201.1 1639.81  5319.7 1640.23  5529.8 1643.18  5539.8 1642.46  5862.7 1643.89
#Mann=3,-1,0
  4165.1    0.05       0  4961.4    0.03       0  4969.5    0.05       0
Bank Sta=4961.4,4969.5
Exp/Cntr=0.3,0.1

Chan Stop Cuts=-1