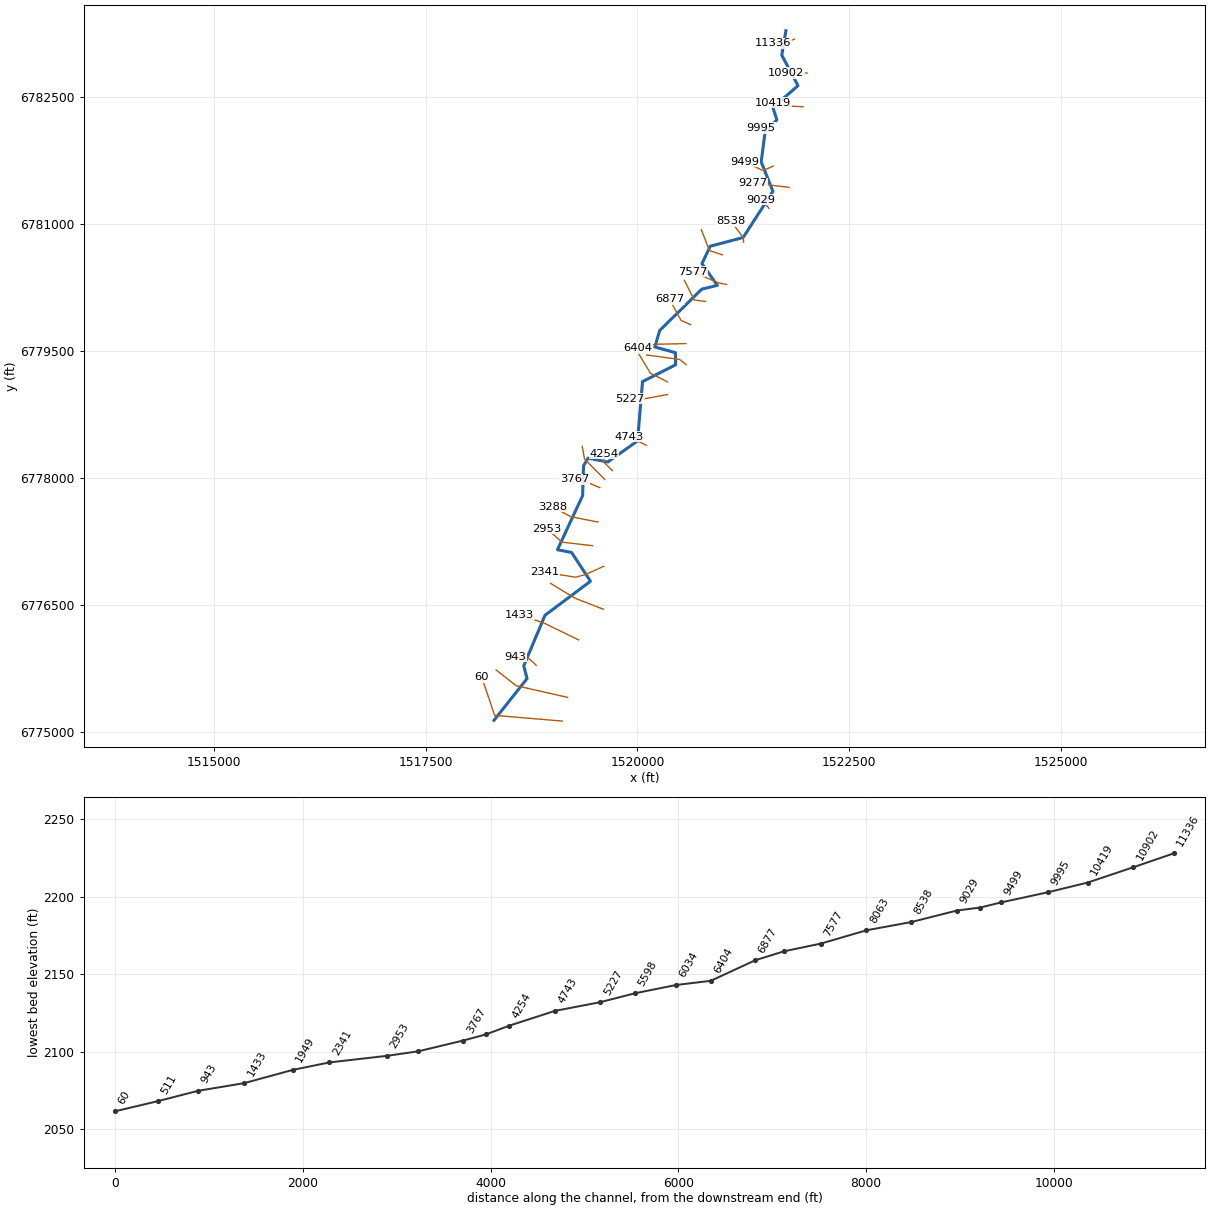
--- Horse Fall Creek.prj (project) ---

Proj Title=Horse Fall Creek Base Level Engineering
Current Plan=p01
Default Exp/Contr=0.3,0.1
English Units
Geom File=g01
Flow File=f01
Plan File=p01
BEGIN DESCRIPTION:
Horse Fall Creek
END DESCRIPTION:

--- Horse Fall Creek.p01 (plan) ---

Plan Title=Multiple Run
Short Identifier=Multiple
Geom File=g01
Flow File=f01
Subcritical Flow
K Sum by GR= 0
Std Step Tol= 0.01
Critical Tol= 0.01
Num of Std Step Trials= 20
Max Error Tol= 0.3
Flow Tol Ratio= 0.001
Split Flow NTrial= 30
Split Flow Tol= 0.02
Split Flow Ratio= 0.02
Log Output Level= 0
Friction Slope Method= 1
Unsteady Friction Slope Method= 2
Unsteady Bridges Friction Slope Method= 1
Parabolic Critical Depth
Global Vel Dist=  1 , 1 , 1
Global Log Level= 0
CheckData=True
Encroach Param= -1, 0, 0, 0
BEGIN DESCRIPTION:
Multiple Run
END DESCRIPTION:

--- Horse Fall Creek.f01 (steady flow) ---

Flow Title=Multiple
Number of Profiles=7
Profile Names=10-year,25-year,50-year,1pct_min,100-year,1pct_plu,500-year
River Rch & RM= Horse Fall Creek,Reach-1,11336
     255     357     442     340     545     750     839
River Rch & RM= Horse Fall Creek,Reach-1,6404
     518     755     961     759    1220    1670    1970
Boundary for River Rch & Prof#=Horse Fall Creek,Reach-1,1
Up Type=0
Dn Type=3
Dn Slope=0.005
Boundary for River Rch & Prof#=Horse Fall Creek,Reach-1,2
Up Type=0
Dn Type=3
Dn Slope=0.005
Boundary for River Rch & Prof#=Horse Fall Creek,Reach-1,3
Up Type=0
Dn Type=3
Dn Slope=0.005
Boundary for River Rch & Prof#=Horse Fall Creek,Reach-1,4
Up Type=0
Dn Type=3
Dn Slope=0.005
Boundary for River Rch & Prof#=Horse Fall Creek,Reach-1,5
Up Type=0
Dn Type=3
Dn Slope=0.005
Boundary for River Rch & Prof#=Horse Fall Creek,Reach-1,6
Up Type=0
Dn Type=3
Dn Slope=0.005
Boundary for River Rch & Prof#=Horse Fall Creek,Reach-1,7
Up Type=0
Dn Type=3
Dn Slope=0.005

--- Horse Fall Creek.g01 (geometry) ---

Geom Title=Existing Conditions

River Reach=Horse Fall Creek,Reach-1
Reach XY= 30
      1521755.00      6783288.00      1521705.94      6782998.48
      1521897.69      6782637.90      1521601.46      6782378.86
      1521647.39      6782234.67      1521508.54      6782086.54
      1521462.53      6781737.99      1521601.26      6781389.56
      1521249.59      6780843.17      1520860.72      6780740.58
      1520762.77      6780534.59      1520944.98      6780277.95
      1520760.44      6780232.81      1520262.91      6779744.15
      1520206.37      6779549.53      1520449.84      6779482.59
      1520451.48      6779339.46      1520060.47      6779140.45
      1520001.47      6778439.45      1519649.03      6778190.14
      1519416.85      6778236.50      1519363.07      6778144.12
      1519352.93      6777793.86      1519055.05      6777153.75
      1519221.80      6777121.58      1519445.78      6776781.41
      1518908.16      6776379.68      1518656.97      6775782.11
      1518695.99      6775630.98      1518305.00      6775138.00

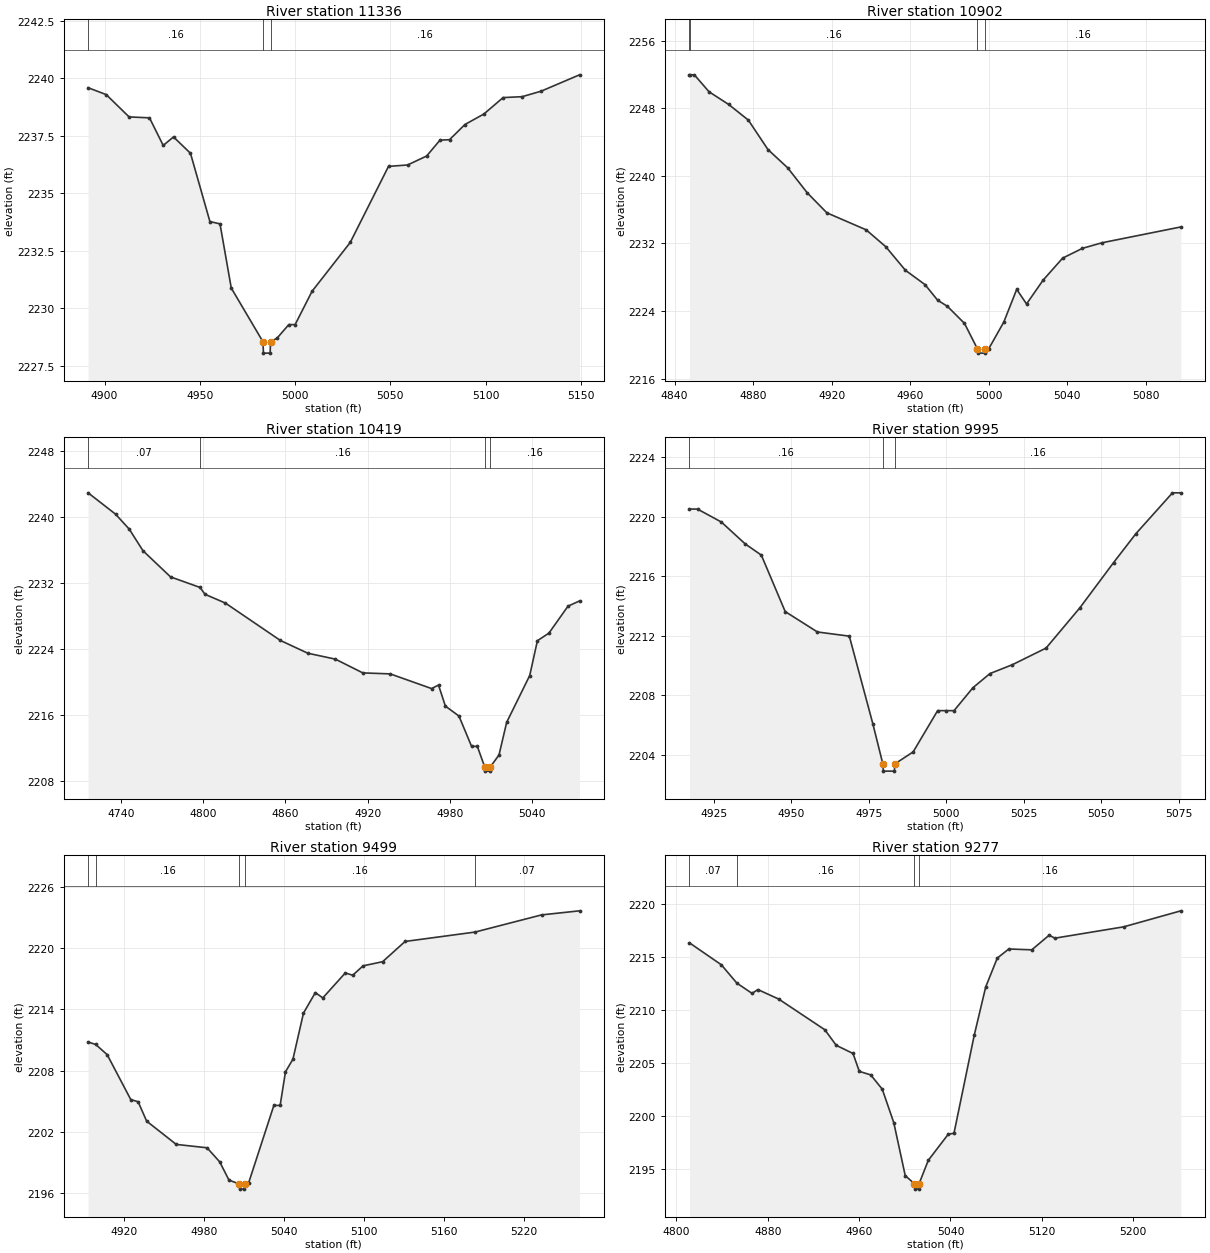
Type RM Length L Ch R = 1,11336,434,434,434
BEGIN DESCRIPTION:
221
END DESCRIPTION:
XS GIS Cut Line= 3
      1521854.99      6783188.00      1521753.83      6783148.48
      1521605.00      6783138.00
#Sta/Elev= 30
  4891.4 2239.58  4900.9 2239.28  4912.9 2238.31  4923.6 2238.27  4930.8 2237.07
  4936.2 2237.44  4945.1 2236.73  4955.3 2233.76  4960.6 2233.66  4966.5 2230.87
  4983.1 2228.54  4983.4 2228.04  4986.9 2228.04  4987.1 2228.54  4990.5 2228.69
  4996.7 2229.28  5000.0 2229.28  5008.9 2230.73  5028.9 2232.85  5049.0 2236.16
  5059.0 2236.22  5069.0 2236.61  5076.0 2237.30  5081.0 2237.32  5089.1 2237.98
  5099.1 2238.44  5109.1 2239.15  5119.1 2239.19  5129.1 2239.43  5149.2 2240.14
#Mann=3,-1,0
  4891.4    0.16       0  4983.1    0.07       0  4987.1    0.16       0
Bank Sta=4983.1,4987.1
Exp/Cntr=0.3,0.1

Type RM Length L Ch R = 1,10902,483,483,483
BEGIN DESCRIPTION:
220
END DESCRIPTION:
XS GIS Cut Line= 3
      1522004.96      6782788.00      1521852.67      6782782.03
      1521754.96      6782788.00
#Sta/Elev= 30
  4847.6 2251.96  4847.8 2251.96  4850.1 2251.96  4857.6 2249.95  4867.6 2248.45
  4877.6 2246.60  4887.6 2243.11  4897.6 2240.96  4907.6 2237.99  4917.6 2235.62
  4937.6 2233.61  4947.6 2231.61  4957.6 2228.82  4967.6 2227.12  4974.0 2225.28
  4979.0 2224.55  4987.7 2222.53  4994.3 2219.51  4994.6 2219.01  4998.1 2219.01
  4998.3 2219.51  5000.0 2219.51  5007.7 2222.68  5014.3 2226.56  5019.3 2224.83
  5027.7 2227.64  5037.7 2230.26  5047.8 2231.42  5057.8 2232.08  5097.9 2233.95
#Mann=4,-1,0
  4847.6    0.07       0  4847.8    0.16       0  4994.3    0.07       0
  4998.3    0.16       0
Bank Sta=4994.3,4998.3
Exp/Cntr=0.3,0.1

Type RM Length L Ch R = 1,10419,424,424,424
BEGIN DESCRIPTION:
219
END DESCRIPTION:
XS GIS Cut Line= 3
      1521954.96      6782388.00      1521671.65      6782404.65
      1521605.03      6782437.99
#Sta/Elev= 30
  4716.2 2242.98  4736.2 2240.39  4746.2 2238.57  4756.2 2235.95  4776.3 2232.77
  4797.8 2231.49  4801.4 2230.66  4816.3 2229.59  4856.4 2225.05  4876.4 2223.50
  4896.5 2222.78  4916.5 2221.11  4936.5 2220.99  4966.6 2219.21  4971.7 2219.63
  4976.7 2217.08  4986.6 2215.87  4995.8 2212.19  5000.0 2212.19  5005.4 2209.68
  5005.7 2209.18  5009.2 2209.18  5009.4 2209.68  5015.8 2211.14  5021.4 2215.11
  5038.2 2220.79  5043.8 2225.02  5052.2 2225.94  5066.1 2229.21  5074.5 2229.85
#Mann=4,-1,0
  4716.2    0.07       0  4797.8    0.16       0  5005.4    0.07       0
  5009.4    0.16       0
Bank Sta=5005.4,5009.4
Exp/Cntr=0.3,0.1

Type RM Length L Ch R = 1,9995,496,496,496
BEGIN DESCRIPTION:
218
END DESCRIPTION:
XS GIS Cut Line= 3
      1521605.02      6782088.00      1521524.61      6782108.16
      1521455.03      6782137.99
#Sta/Elev= 26
  4917.1 2220.51  4919.7 2220.51  4927.4 2219.64  4935.1 2218.17  4940.3 2217.42
  4948.0 2213.63  4958.4 2212.26  4968.7 2211.98  4976.3 2206.09  4979.5 2203.42
  4979.7 2202.92  4983.2 2202.92  4983.5 2203.42  4989.3 2204.21  4997.2 2206.98
  5000.0 2206.98  5002.5 2206.98  5008.6 2208.52  5014.1 2209.47  5021.3 2210.06
  5032.2 2211.18  5043.1 2213.88  5054.0 2216.92  5061.2 2218.86  5073.0 2221.60
  5075.7 2221.60
#Mann=3,-1,0
  4917.1    0.16       0  4979.5    0.07       0  4983.5    0.16       0
Bank Sta=4979.5,4983.5
Exp/Cntr=0.3,0.1

Type RM Length L Ch R = 1,9499,222,222,222
BEGIN DESCRIPTION:
217
END DESCRIPTION:
XS GIS Cut Line= 4
      1521605.02      6781688.01      1521507.47      6781644.05
      1521470.70      6781639.81      1521269.49      6781739.37
#Sta/Elev= 30
  4893.0 2210.80  4898.7 2210.56  4907.3 2209.56  4925.0 2205.16  4930.5 2204.95
  4936.9 2203.05  4959.1 2200.77  4982.2 2200.44  4991.7 2199.06  4998.6 2197.28
  5006.4 2196.89  5006.6 2196.39  5010.1 2196.39  5010.4 2196.89  5013.4 2197.01
  5032.3 2204.59  5037.0 2204.59  5041.0 2207.88  5046.6 2209.12  5054.5 2213.63
  5063.4 2215.64  5069.0 2215.12  5085.9 2217.57  5091.4 2217.34  5099.2 2218.26
  5113.9 2218.67  5130.7 2220.65  5183.2 2221.57  5233.0 2223.25  5261.5 2223.65
#Mann=5,-1,0
  4893.0    0.07       0  4898.7    0.16       0  5006.4    0.07       0
  5010.4    0.16       0  5183.2    0.07       0
Bank Sta=5006.4,5010.4
Exp/Cntr=0.3,0.1

Type RM Length L Ch R = 1,9277,248,248,248
BEGIN DESCRIPTION:
859
END DESCRIPTION:
XS GIS Cut Line= 2
      1521792.66      6781436.42      1521365.37      6781486.38
#Sta/Elev= 30
  4811.5 2216.32  4839.4 2214.25  4853.0 2212.52  4866.3 2211.55  4871.4 2211.91
  4889.7 2211.01  4930.0 2208.12  4940.0 2206.65  4954.7 2205.88  4960.2 2204.19
  4970.2 2203.86  4980.3 2202.51  4990.4 2199.35  5000.4 2194.36  5008.5 2193.58
  5008.8 2193.08  5012.3 2193.08  5012.5 2193.58  5020.6 2195.80  5038.0 2198.25
  5043.1 2198.36  5060.9 2207.64  5070.9 2212.17  5081.0 2214.88  5091.1 2215.74
  5111.2 2215.66  5126.4 2217.04  5131.4 2216.76  5191.7 2217.83  5241.7 2219.34
#Mann=4,-1,0
  4811.5    0.07       0  4853.0    0.16       0  5008.5    0.07       0
  5012.5    0.16       0
Bank Sta=5008.5,5012.5
Exp/Cntr=0.3,0.1

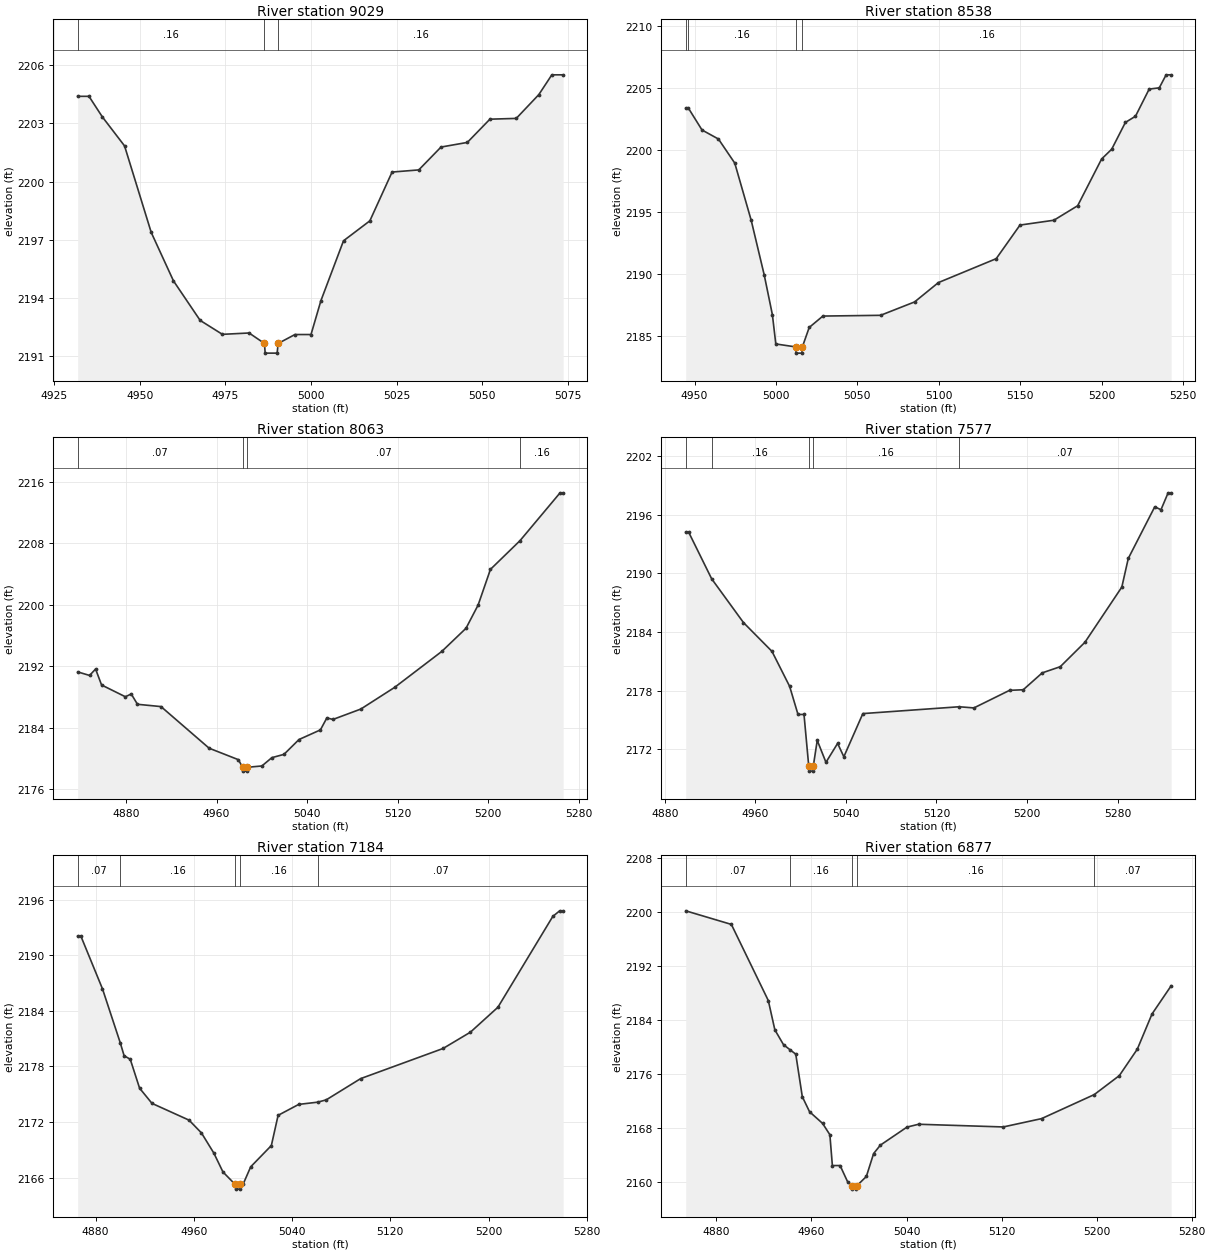
Type RM Length L Ch R = 1,9029,491,491,491
BEGIN DESCRIPTION:
216
END DESCRIPTION:
XS GIS Cut Line= 3
      1521555.01      6781187.99      1521511.10      6781240.19
      1521455.01      6781287.99
#Sta/Elev= 27
  4931.8 2204.40  4935.1 2204.40  4939.0 2203.34  4945.5 2201.84  4953.3 2197.37
  4959.8 2194.87  4967.6 2192.83  4974.1 2192.11  4981.9 2192.18  4986.4 2191.64
  4986.6 2191.14  4990.1 2191.14  4990.4 2191.64  4995.3 2192.10  5000.0 2192.10
  5002.9 2193.85  5009.5 2196.94  5017.2 2197.97  5023.7 2200.49  5031.5 2200.60
  5038.0 2201.78  5045.7 2202.02  5052.3 2203.22  5060.0 2203.26  5066.6 2204.49
  5070.4 2205.51  5073.7 2205.51
#Mann=3,-1,0
  4931.8    0.16       0  4986.4    0.07       0  4990.4    0.16       0
Bank Sta=4986.4,4990.4
Exp/Cntr=0.3,0.1

Type RM Length L Ch R = 1,8538,475,475,475
BEGIN DESCRIPTION:
215
END DESCRIPTION:
XS GIS Cut Line= 3
      1521255.00      6780788.04      1521249.59      6780843.17
      1521105.01      6781037.98
#Sta/Elev= 30
  4944.6 2203.40  4946.3 2203.40  4954.6 2201.65  4964.7 2200.92  4974.7 2198.98
  4984.8 2194.36  4992.8 2189.95  4997.8 2186.75  4999.9 2184.39  5012.2 2184.15
  5012.4 2183.65  5015.9 2183.65  5016.2 2184.15  5020.4 2185.72  5028.8 2186.64
  5064.2 2186.70  5085.1 2187.78  5099.7 2189.34  5135.2 2191.27  5149.8 2193.98
  5170.6 2194.37  5185.2 2195.54  5199.9 2199.31  5206.1 2200.10  5214.5 2202.26
  5220.7 2202.76  5229.1 2204.95  5235.3 2205.05  5239.5 2206.10  5242.6 2206.10
#Mann=4,-1,0
  4944.6    0.07       0  4946.3    0.16       0  5012.2    0.07       0
  5016.2    0.16       0
Bank Sta=5012.2,5016.2
Exp/Cntr=0.3,0.1

Type RM Length L Ch R = 1,8063,486,486,486
BEGIN DESCRIPTION:
214
END DESCRIPTION:
XS GIS Cut Line= 3
      1521005.04      6780637.99      1520850.80      6780689.77
      1520754.99      6780938.02
#Sta/Elev= 30
  4837.3 2191.25  4847.8 2190.79  4853.1 2191.62  4858.4 2189.55  4879.4 2188.02
  4884.6 2188.38  4890.1 2187.04  4910.9 2186.74  4953.4 2181.33  4979.2 2179.84
  4983.0 2178.85  4983.3 2178.35  4986.8 2178.35  4987.0 2178.85  5000.0 2179.02
  5008.8 2180.10  5019.5 2180.53  5032.8 2182.46  5051.7 2183.71  5057.4 2185.27
  5062.8 2185.07  5087.4 2186.42  5117.3 2189.24  5158.9 2193.91  5180.3 2196.92
  5191.0 2199.94  5201.9 2204.58  5228.0 2208.31  5263.4 2214.53  5266.1 2214.53
#Mann=4,-1,0
  4837.3    0.07       0  4983.0    0.07       0  4987.0    0.07       0
  5228.0    0.16       0
Bank Sta=4983,4987
Exp/Cntr=0.3,0.1

Type RM Length L Ch R = 1,7577,393,393,393
BEGIN DESCRIPTION:
213
END DESCRIPTION:
XS GIS Cut Line= 3
      1521055.02      6780288.00      1520955.52      6780308.05
      1520655.02      6780437.99
#Sta/Elev= 30
  4898.5 2194.22  4901.1 2194.22  4921.4 2189.45  4949.5 2184.97  4974.7 2182.02
  4990.3 2178.44  4997.7 2175.56  5003.0 2175.56  5007.2 2170.26  5007.5 2169.76
  5011.0 2169.76  5011.2 2170.26  5014.7 2172.91  5022.4 2170.66  5032.7 2172.60
  5038.2 2171.23  5055.0 2175.65  5140.1 2176.35  5153.1 2176.23  5184.6 2178.03
  5196.7 2178.09  5213.5 2179.82  5229.4 2180.45  5251.2 2182.95  5283.8 2188.60
  5289.5 2191.53  5312.9 2196.82  5318.4 2196.52  5324.7 2198.25  5327.4 2198.25
#Mann=5,-1,0
  4898.5    0.07       0  4921.4    0.16       0  5007.2    0.07       0
  5011.2    0.16       0  5140.1    0.07       0
Bank Sta=5007.2,5011.2
Exp/Cntr=0.3,0.1

Type RM Length L Ch R = 1,7184,307,307,307
BEGIN DESCRIPTION:
212
END DESCRIPTION:
XS GIS Cut Line= 3
      1520805.04      6780087.99      1520671.49      6780104.74
      1520555.01      6780337.98
#Sta/Elev= 30
  4865.4 2192.06  4868.0 2192.06  4885.6 2186.37  4900.1 2180.54  4903.2 2179.16
  4908.2 2178.78  4915.8 2175.66  4925.9 2174.02  4956.1 2172.21  4966.2 2170.83
  4976.3 2168.65  4983.7 2166.62  4993.7 2165.27  4994.0 2164.77  4997.5 2164.77
  4997.7 2165.27  5000.0 2165.27  5006.3 2167.18  5023.1 2169.47  5028.6 2172.73
  5045.4 2173.91  5060.8 2174.15  5067.8 2174.40  5095.8 2176.69  5162.9 2179.94
  5185.2 2181.70  5207.6 2184.39  5252.3 2194.19  5257.9 2194.79  5260.7 2194.79
#Mann=5,-1,0
  4865.4    0.07       0  4900.1    0.16       0  4993.7    0.07       0
  4997.7    0.16       0  5060.8    0.07       0
Bank Sta=4993.7,4997.7
Exp/Cntr=0.3,0.1

Type RM Length L Ch R = 1,6877,473,473,473
BEGIN DESCRIPTION:
211
END DESCRIPTION:
XS GIS Cut Line= 3
      1520630.02      6779812.99      1520516.08      6779864.24
      1520379.99      6780113.01
#Sta/Elev= 30
  4854.2 2200.14  4892.6 2198.13  4923.7 2186.86  4929.2 2182.53  4936.5 2180.33
  4942.3 2179.54  4946.8 2178.93  4952.3 2172.64  4958.4 2170.41  4969.4 2168.68
  4975.5 2167.01  4977.6 2162.45  4984.1 2162.45  4990.5 2160.02  4994.2 2159.46
  4994.4 2158.96  4997.9 2158.96  4998.2 2159.46  5006.2 2160.83  5012.3 2164.22
  5018.0 2165.47  5040.4 2168.14  5050.2 2168.56  5121.4 2168.16  5153.6 2169.39
  5198.0 2172.95  5219.1 2175.76  5234.2 2179.67  5246.6 2184.88  5262.7 2189.05
#Mann=5,-1,0
  4854.2    0.07       0  4942.3    0.16       0  4994.2    0.07       0
  4998.2    0.16       0  5198.0    0.07       0
Bank Sta=4994.2,4998.2
Exp/Cntr=0.3,0.1

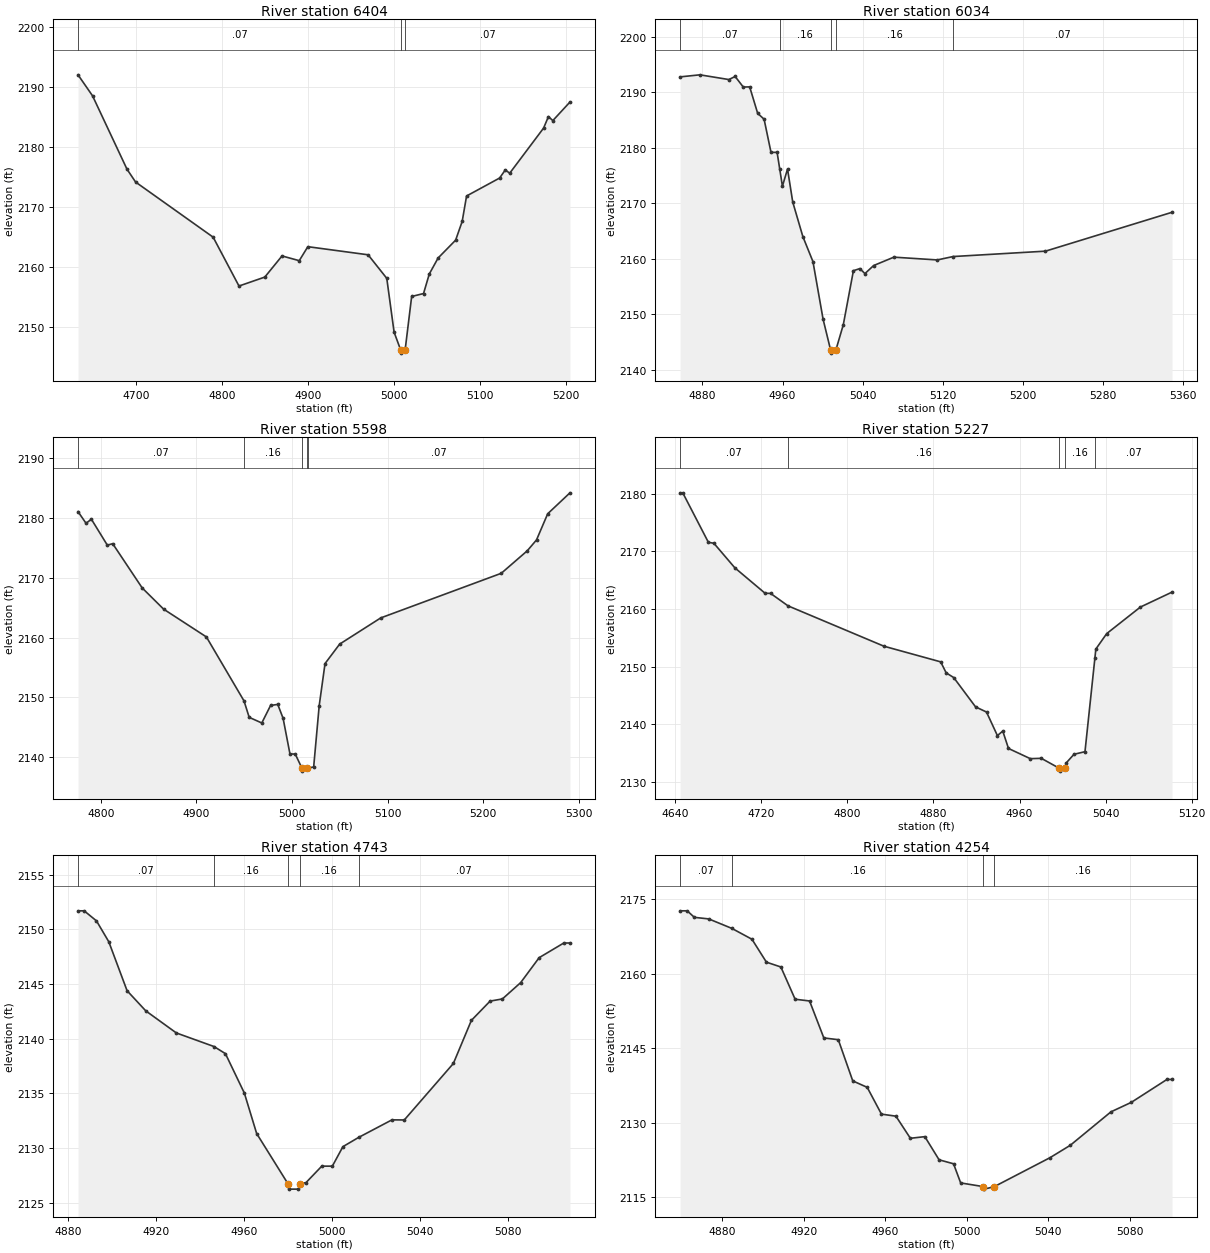
Type RM Length L Ch R = 1,6404,370,370,370
BEGIN DESCRIPTION:
210
END DESCRIPTION:
XS GIS Cut Line= 3
      1520571.93      6779590.01      1520213.37      6779581.37
      1520005.00      6779538.00
#Sta/Elev= 30
  4632.9 2192.04  4649.8 2188.54  4689.8 2176.33  4699.8 2174.19  4789.9 2165.01
  4819.9 2156.88  4849.9 2158.37  4869.9 2161.89  4889.9 2161.10  4899.9 2163.43
  4969.9 2162.08  4991.6 2158.16  5000.1 2149.20  5007.8 2146.21  5008.2 2145.71
  5012.9 2146.21  5020.5 2155.14  5034.3 2155.63  5041.0 2158.89  5051.2 2161.54
  5071.6 2164.52  5079.2 2167.64  5084.3 2171.87  5122.7 2174.86  5129.3 2176.21
  5134.4 2175.66  5173.8 2183.18  5179.4 2185.09  5184.5 2184.42  5204.4 2187.51
#Mann=3,-1,0
  4632.9    0.07       0  5007.8    0.07       0  5012.9    0.07       0
Bank Sta=5007.8,5012.9
Exp/Cntr=0.3,0.1

Type RM Length L Ch R = 1,6034,436,436,436
BEGIN DESCRIPTION:
855
END DESCRIPTION:
XS GIS Cut Line= 3
      1520576.32      6779341.32      1520500.50      6779401.63
      1520109.71      6779455.00
#Sta/Elev= 30
  4857.7 2192.74  4877.5 2193.11  4906.4 2192.26  4912.7 2192.81  4920.8 2190.91
  4927.2 2190.94  4935.2 2186.17  4941.6 2185.12  4948.5 2179.15  4954.6 2179.15
  4957.2 2176.16  4959.9 2173.05  4965.0 2176.15  4970.2 2170.21  4980.3 2163.99
  4990.4 2159.48  5000.5 2149.12  5008.1 2143.50  5008.5 2143.00  5013.2 2143.50
  5020.7 2148.11  5030.8 2157.84  5037.2 2158.22  5042.3 2157.32  5051.0 2158.77
  5071.2 2160.28  5114.6 2159.78  5130.3 2160.39  5222.6 2161.36  5349.0 2168.36
#Mann=5,-1,0
  4857.7    0.07       0  4957.2    0.16       0  5008.1    0.07       0
  5013.2    0.16       0  5130.3    0.07       0
Bank Sta=5008.1,5013.2
Exp/Cntr=0.3,0.1

Type RM Length L Ch R = 1,5598,371,371,371
BEGIN DESCRIPTION:
209
END DESCRIPTION:
XS GIS Cut Line= 3
      1520355.02      6779137.99      1520153.79      6779239.53
      1520005.01      6779487.99
#Sta/Elev= 30
  4776.0 2181.05  4784.4 2179.10  4790.0 2179.78  4806.7 2175.44  4812.3 2175.69
  4843.2 2168.29  4865.6 2164.75  4910.4 2160.10  4949.8 2149.40  4955.2 2146.66
  4968.4 2145.72  4977.6 2148.65  4985.1 2148.82  4990.7 2146.50  4997.9 2140.53
  5003.4 2140.53  5010.4 2138.17  5010.8 2137.67  5015.5 2138.17  5017.0 2138.21
  5022.7 2138.36  5028.5 2148.62  5034.6 2155.65  5049.9 2158.90  5092.9 2163.28
  5219.1 2170.74  5246.3 2174.50  5256.0 2176.32  5267.7 2180.69  5291.0 2184.19
#Mann=5,-1,0
  4776.0    0.07       0  4949.8    0.16       0  5010.4    0.07       0
  5015.5    0.16       0  5017.0    0.07       0
Bank Sta=5010.4,5015.5
Exp/Cntr=0.3,0.1

Type RM Length L Ch R = 1,5227,484,484,484
BEGIN DESCRIPTION:
208
END DESCRIPTION:
XS GIS Cut Line= 3
      1520354.99      6778988.00      1520005.52      6778922.78
      1519904.97      6778938.00
#Sta/Elev= 30
  4644.5 2180.15  4647.0 2180.15  4670.8 2171.57  4675.9 2171.41  4695.4 2167.15
  4723.5 2162.74  4728.6 2162.72  4744.8 2160.56  4834.0 2153.56  4886.7 2150.85
  4891.8 2148.94  4898.8 2148.13  4919.1 2143.05  4929.3 2142.15  4939.4 2138.07
  4944.4 2138.85  4949.7 2135.84  4970.0 2134.07  4980.2 2134.13  4996.9 2132.41
  4997.3 2131.91  5002.0 2132.41  5003.5 2133.36  5010.6 2134.83  5020.8 2135.28
  5030.0 2151.48  5030.9 2153.07  5041.0 2155.75  5072.3 2160.35  5101.7 2162.94
#Mann=5,-1,0
  4644.5    0.07       0  4744.8    0.16       0  4996.9    0.07       0
  5002.0    0.16       0  5030.0    0.07       0
Bank Sta=4996.9,5002
Exp/Cntr=0.3,0.1

Type RM Length L Ch R = 1,4743,489,489,489
BEGIN DESCRIPTION:
207
END DESCRIPTION:
XS GIS Cut Line= 3
      1520104.99      6778388.01      1520001.47      6778439.45
      1519905.00      6778488.00
#Sta/Elev= 30
  4884.4 2151.69  4887.2 2151.69  4892.8 2150.77  4898.4 2148.86  4906.7 2144.39
  4915.2 2142.55  4929.1 2140.53  4946.2 2139.29  4951.4 2138.64  4960.0 2135.04
  4965.6 2131.34  4979.8 2126.76  4980.2 2126.26  4984.6 2126.26  4985.1 2126.76
  4988.0 2126.85  4995.2 2128.36  5000.0 2128.36  5004.8 2130.14  5011.9 2130.98
  5027.1 2132.59  5032.7 2132.58  5055.0 2137.74  5063.2 2141.68  5071.7 2143.44
  5077.3 2143.64  5085.6 2145.13  5094.0 2147.41  5105.2 2148.75  5108.0 2148.75
#Mann=5,-1,0
  4884.4    0.07       0  4946.2    0.16       0  4979.8    0.07       0
  4985.1    0.16       0  5011.9    0.07       0
Bank Sta=4979.8,4985.1
Exp/Cntr=0.3,0.1

Type RM Length L Ch R = 1,4254,246,246,246
BEGIN DESCRIPTION:
206
END DESCRIPTION:
XS GIS Cut Line= 3
      1519704.97      6778088.03      1519605.00      6778187.18
      1519605.00      6778287.98
#Sta/Elev= 30
  4859.2 2172.65  4862.7 2172.65  4866.2 2171.34  4873.3 2171.02  4884.6 2169.12
  4894.5 2166.93  4901.6 2162.32  4908.7 2161.35  4915.7 2154.86  4922.8 2154.51
  4929.8 2147.07  4936.9 2146.72  4944.0 2138.43  4951.1 2137.13  4958.1 2131.74
  4965.2 2131.33  4972.3 2126.88  4979.4 2127.21  4986.4 2122.55  4993.5 2121.75
  4997.0 2117.90  5008.2 2117.15  5008.6 2116.65  5013.5 2117.15  5040.8 2122.96
  5050.8 2125.46  5070.8 2132.20  5080.8 2134.11  5098.3 2138.72  5100.8 2138.72
#Mann=4,-1,0
  4859.2    0.07       0  4884.6    0.16       0  5008.2    0.07       0
  5013.5    0.16       0
Bank Sta=5008.2,5013.5
Exp/Cntr=0.3,0.1

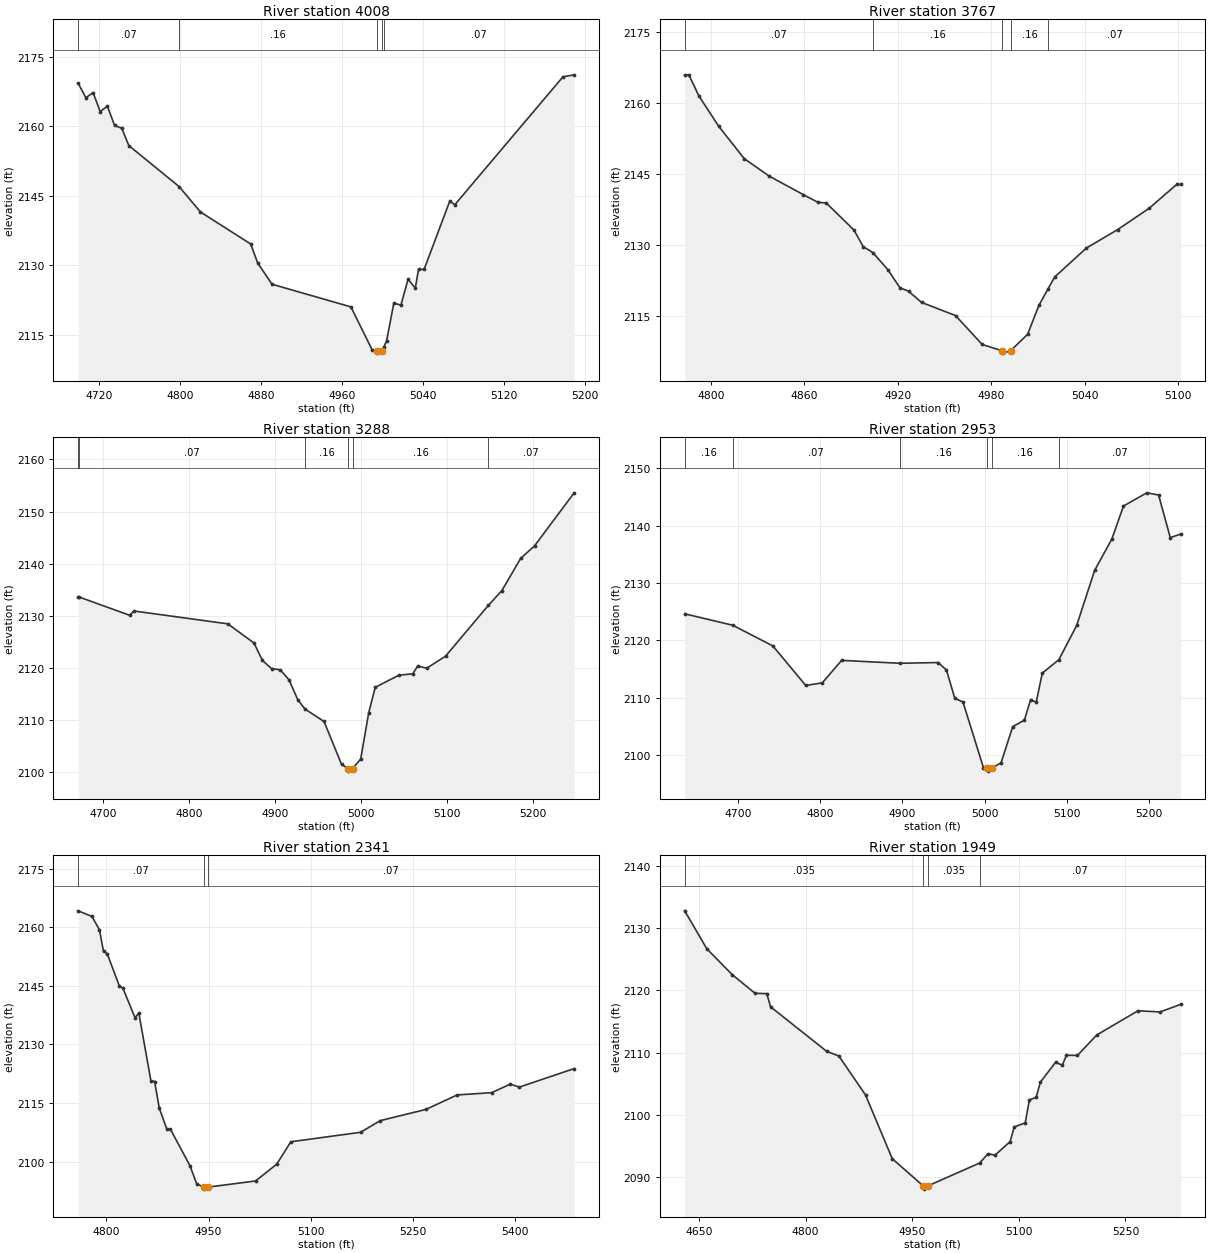
Type RM Length L Ch R = 1,4008,241,241,241
BEGIN DESCRIPTION:
854
END DESCRIPTION:
XS GIS Cut Line= 3
      1519613.16      6777985.41      1519375.43      6778224.86
      1519348.17      6778374.78
#Sta/Elev= 30
  4699.5 2169.22  4707.1 2166.10  4714.2 2167.23  4721.2 2163.12  4728.3 2164.30
  4735.4 2160.14  4742.5 2159.53  4749.5 2155.80  4799.1 2146.97  4820.2 2141.48
  4869.8 2134.59  4876.8 2130.47  4890.9 2125.90  4968.8 2121.02  4989.9 2111.71
  4994.4 2111.55  4994.8 2111.05  4999.7 2111.55  5001.2 2112.29  5004.1 2113.73
  5011.2 2121.83  5018.2 2121.40  5025.3 2127.00  5032.4 2125.05  5035.6 2129.10
  5041.1 2129.10  5066.4 2143.79  5071.5 2143.06  5178.2 2170.61  5189.3 2171.05
#Mann=5,-1,0
  4699.5    0.07       0  4799.1    0.16       0  4994.4    0.07       0
  4999.7    0.16       0  5001.2    0.07       0
Bank Sta=4994.4,4999.7
Exp/Cntr=0.3,0.1

Type RM Length L Ch R = 1,3767,479,479,479
BEGIN DESCRIPTION:
205
END DESCRIPTION:
XS GIS Cut Line= 3
      1519555.02      6777887.99      1519355.49      6777972.80
      1519255.04      6777987.99
#Sta/Elev= 30
  4783.2 2165.93  4785.9 2165.93  4792.3 2161.48  4805.0 2155.08  4821.4 2148.23
  4837.5 2144.52  4859.3 2140.63  4868.7 2139.00  4874.1 2138.85  4891.9 2133.13
  4897.8 2129.63  4904.0 2128.38  4913.6 2124.78  4921.4 2120.94  4926.9 2120.22
  4935.3 2117.84  4957.1 2115.07  4974.2 2108.96  4987.0 2107.63  4987.4 2107.13
  4992.4 2107.63  5003.4 2111.12  5010.6 2117.22  5016.6 2120.77  5020.7 2123.20
  5041.0 2129.31  5061.2 2133.23  5081.4 2137.73  5099.1 2142.78  5101.6 2142.78
#Mann=5,-1,0
  4783.2    0.07       0  4904.0    0.16       0  4987.0    0.07       0
  4992.4    0.16       0  5016.6    0.07       0
Bank Sta=4987,4992.4
Exp/Cntr=0.3,0.1

Type RM Length L Ch R = 1,3288,335,335,335
BEGIN DESCRIPTION:
204
END DESCRIPTION:
XS GIS Cut Line= 3
      1519535.83      6777480.97      1519213.14      6777544.06
      1518994.73      6777662.37
#Sta/Elev= 30
  4671.2 2133.58  4672.3 2133.58  4731.0 2130.08  4736.1 2130.90  4845.3 2128.43
  4875.8 2124.75  4885.6 2121.40  4896.2 2119.84  4906.4 2119.60  4916.6 2117.67
  4926.8 2113.83  4935.2 2112.07  4957.3 2109.68  4977.7 2101.44  4985.2 2100.65
  4985.6 2100.15  4990.7 2100.65  5000.0 2102.50  5009.3 2111.36  5016.9 2116.24
  5044.4 2118.57  5060.6 2118.84  5066.3 2120.34  5076.8 2119.91  5098.7 2122.22
  5148.5 2131.97  5164.3 2134.82  5186.1 2140.99  5202.3 2143.41  5248.4 2153.59
#Mann=6,-1,0
  4671.2    0.16       0  4672.3    0.07       0  4935.2    0.16       0
  4985.2    0.07       0  4990.7    0.16       0  5148.5    0.07       0
Bank Sta=4985.2,4990.7
Exp/Cntr=0.3,0.1

Type RM Length L Ch R = 1,2953,612,612,612
BEGIN DESCRIPTION:
203
END DESCRIPTION:
XS GIS Cut Line= 3
      1519471.27      6777201.20      1519108.99      6777243.19
      1518930.19      6777401.03
#Sta/Elev= 30
  4635.3 2124.63  4693.8 2122.64  4742.6 2119.03  4782.5 2112.15  4802.7 2112.60
  4826.2 2116.52  4897.0 2116.01  4943.6 2116.14  4953.7 2114.84  4963.8 2109.91
  4973.8 2109.26  4998.7 2097.81  5003.2 2097.72  5003.7 2097.22  5008.7 2097.72
  5020.1 2098.67  5034.3 2104.97  5048.5 2106.11  5056.1 2109.68  5062.8 2109.22
  5070.3 2114.30  5090.4 2116.64  5112.1 2122.60  5133.9 2132.19  5154.8 2137.64
  5169.0 2143.41  5197.4 2145.71  5211.7 2145.33  5225.9 2137.92  5238.5 2138.51
#Mann=6,-1,0
  4635.3    0.16       0  4693.8    0.07       0  4897.0    0.16       0
  5003.2    0.07       0  5008.7    0.16       0  5090.4    0.07       0
Bank Sta=5003.2,5008.7
Exp/Cntr=0.3,0.1

Type RM Length L Ch R = 1,2341,392,392,392
BEGIN DESCRIPTION:
202
END DESCRIPTION:
XS GIS Cut Line= 4
      1519603.48      6776958.32      1519383.30      6776859.59
      1519268.36      6776829.19      1518905.62      6776887.60
#Sta/Elev= 30
  4758.7 2164.21  4778.9 2162.76  4789.9 2159.33  4795.8 2153.84  4801.2 2153.26
  4818.9 2145.03  4824.4 2144.36  4842.1 2136.83  4847.6 2138.07  4865.3 2120.75
  4870.8 2120.52  4877.6 2113.72  4888.5 2108.43  4894.0 2108.29  4922.6 2098.99
  4932.4 2094.37  4942.8 2093.47  4943.3 2092.97  4948.7 2093.47  5018.9 2095.06
  5050.0 2099.37  5070.6 2105.09  5172.9 2107.52  5202.0 2110.51  5268.9 2113.38
  5314.7 2117.08  5365.4 2117.67  5392.6 2119.85  5405.9 2119.09  5486.3 2123.82
#Mann=3,-1,0
  4758.7    0.07       0  4942.8    0.07       0  4948.7    0.07       0
Bank Sta=4942.8,4948.7
Exp/Cntr=0.3,0.1

Type RM Length L Ch R = 1,1949,516,516,516
BEGIN DESCRIPTION:
201
END DESCRIPTION:
XS GIS Cut Line= 3
      1519597.28      6776451.06      1519259.53      6776581.98
      1518973.28      6776756.90
#Sta/Elev= 30
  4630.0 2132.76  4661.1 2126.68  4696.8 2122.53  4729.0 2119.53  4745.5 2119.48
  4750.9 2117.36  4830.0 2110.20  4846.9 2109.48  4884.4 2103.23  4922.0 2093.00
  4965.8 2088.62  4966.3 2088.12  4971.8 2088.62  5045.0 2092.31  5056.9 2093.81
  5066.5 2093.56  5087.8 2095.73  5093.6 2098.09  5109.1 2098.75  5114.9 2102.43
  5124.5 2102.85  5130.4 2105.28  5151.7 2108.45  5161.3 2108.01  5167.1 2109.59
  5182.6 2109.57  5209.7 2112.85  5267.8 2116.73  5298.7 2116.54  5327.7 2117.75
#Mann=4,-1,0
  4630.0   0.035       0  4965.8   0.035       0  4971.8   0.035       0
  5045.0    0.07       0
Bank Sta=4965.8,4971.8
Exp/Cntr=0.3,0.1

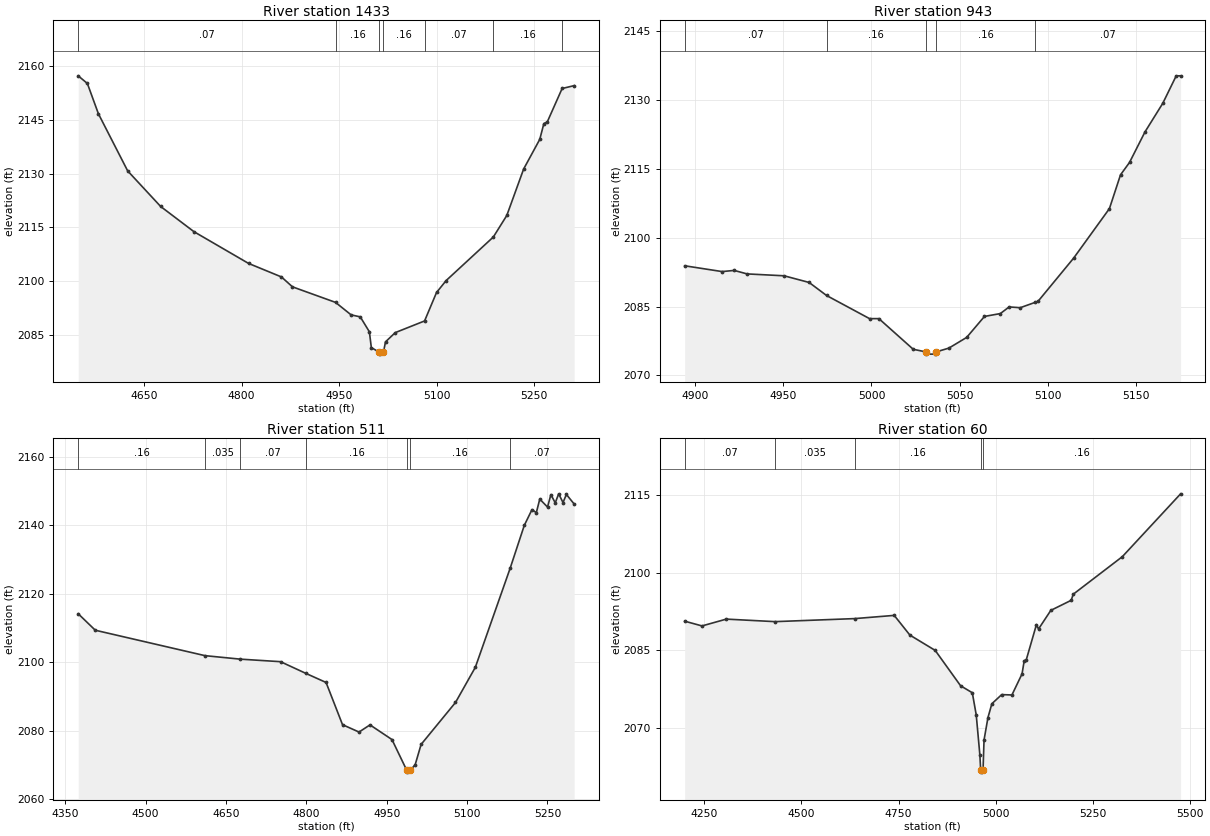
Type RM Length L Ch R = 1,1433,490,490,490
BEGIN DESCRIPTION:
200
END DESCRIPTION:
XS GIS Cut Line= 3
      1519305.04      6776087.98      1518899.44      6776285.64
      1518605.02      6776387.99
#Sta/Elev= 30
  4548.8 2157.33  4562.9 2155.19  4579.9 2146.71  4624.9 2130.76  4675.6 2120.83
  4726.8 2113.79  4810.8 2104.92  4861.4 2101.14  4878.4 2098.37  4944.6 2094.03
  4968.6 2090.54  4982.7 2089.98  4996.7 2085.81  4999.7 2081.40  5012.2 2080.07
  5012.7 2079.57  5018.3 2080.07  5021.5 2083.00  5036.5 2085.58  5081.6 2088.84
  5100.0 2096.79  5114.8 2100.13  5187.4 2112.30  5208.1 2118.32  5234.0 2131.29
  5258.8 2139.58  5265.1 2143.98  5270.4 2144.47  5293.2 2153.79  5311.7 2154.59
#Mann=7,-1,0
  4548.8    0.07       0  4944.6    0.16       0  5012.2    0.07       0
  5018.3    0.16       0  5081.6    0.07       0  5187.4    0.16       0
  5293.2    0.07       0
Bank Sta=5012.2,5018.3
Exp/Cntr=0.3,0.1

Type RM Length L Ch R = 1,943,432,432,432
BEGIN DESCRIPTION:
199
END DESCRIPTION:
XS GIS Cut Line= 3
      1518804.99      6775788.01      1518728.40      6775861.29
      1518555.04      6775887.99
#Sta/Elev= 30
  4894.0 2093.88  4915.2 2092.62  4922.1 2092.87  4929.4 2092.11  4950.4 2091.70
  4964.6 2090.25  4974.5 2087.41  4998.9 2082.37  5004.2 2082.37  5023.7 2075.69
  5030.7 2075.14  5031.2 2074.64  5036.3 2074.64  5036.8 2075.14  5043.9 2075.95
  5054.0 2078.28  5064.1 2082.85  5073.1 2083.47  5078.1 2084.92  5084.4 2084.75
  5092.7 2085.89  5094.5 2086.14  5114.7 2095.55  5135.0 2106.33  5141.3 2113.69
  5146.4 2116.38  5155.2 2123.05  5165.3 2129.28  5172.9 2135.25  5175.4 2135.25
#Mann=5,-1,0
  4894.0    0.07       0  4974.5    0.16       0  5030.7    0.07       0
  5036.8    0.16       0  5092.7    0.07       0
Bank Sta=5030.7,5036.8
Exp/Cntr=0.3,0.1

Type RM Length L Ch R = 1,511,451,451,451
BEGIN DESCRIPTION:
787
END DESCRIPTION:
XS GIS Cut Line= 3
      1519176.15      6775408.81      1518567.40      6775547.17
      1518329.89      6775732.92
#Sta/Elev= 30
  4374.1 2114.14  4406.0 2109.33  4610.8 2101.91  4676.7 2100.89  4751.8 2100.15
  4799.3 2096.72  4836.8 2094.08  4867.5 2081.76  4898.3 2079.61  4918.8 2081.70
  4959.8 2077.42  4987.5 2068.41  4988.0 2067.91  4993.7 2068.41  5003.1 2070.07
  5014.2 2076.00  5078.4 2088.24  5115.4 2098.50  5180.4 2127.41  5206.8 2139.93
  5221.2 2144.55  5229.3 2143.64  5235.7 2147.61  5250.2 2145.29  5256.5 2148.92
  5264.6 2146.51  5271.0 2149.15  5279.1 2146.60  5285.4 2148.97  5299.9 2146.18
#Mann=7,-1,0
  4374.1    0.16       0  4610.8   0.035       0  4676.7    0.07       0
  4799.3    0.16       0  4987.5    0.07       0  4993.7    0.16       0
  5180.4    0.07       0
Bank Sta=4987.5,4993.7
Exp/Cntr=0.3,0.1

Type RM Length L Ch R = 1,60,0,0,0
BEGIN DESCRIPTION:
198
END DESCRIPTION:
XS GIS Cut Line= 3
      1519111.62      6775129.05      1518312.54      6775196.26
      1518162.01      6775644.25
#Sta/Elev= 30
  4200.3 2090.66  4244.8 2089.74  4307.3 2091.06  4432.6 2090.57  4637.5 2091.16
  4738.8 2091.78  4779.0 2087.97  4844.1 2085.00  4909.4 2078.15  4939.5 2076.80
  4949.6 2072.49  4958.9 2064.75  4960.9 2061.93  4961.4 2061.43  4967.1 2061.93
  4969.6 2067.64  4979.7 2072.00  4989.7 2074.67  5015.0 2076.44  5041.3 2076.37
  5067.3 2080.46  5072.8 2082.98  5078.1 2083.17  5104.3 2090.00  5109.6 2089.14
  5141.2 2092.75  5193.6 2094.70  5198.9 2095.88  5325.0 2103.15  5474.8 2115.32
#Mann=5,-1,0
  4200.3    0.07       0  4432.6   0.035       0  4637.5    0.16       0
  4960.9    0.07       0  4967.1    0.16       0
Bank Sta=4960.9,4967.1
Exp/Cntr=0.3,0.1

Chan Stop Cuts=-1