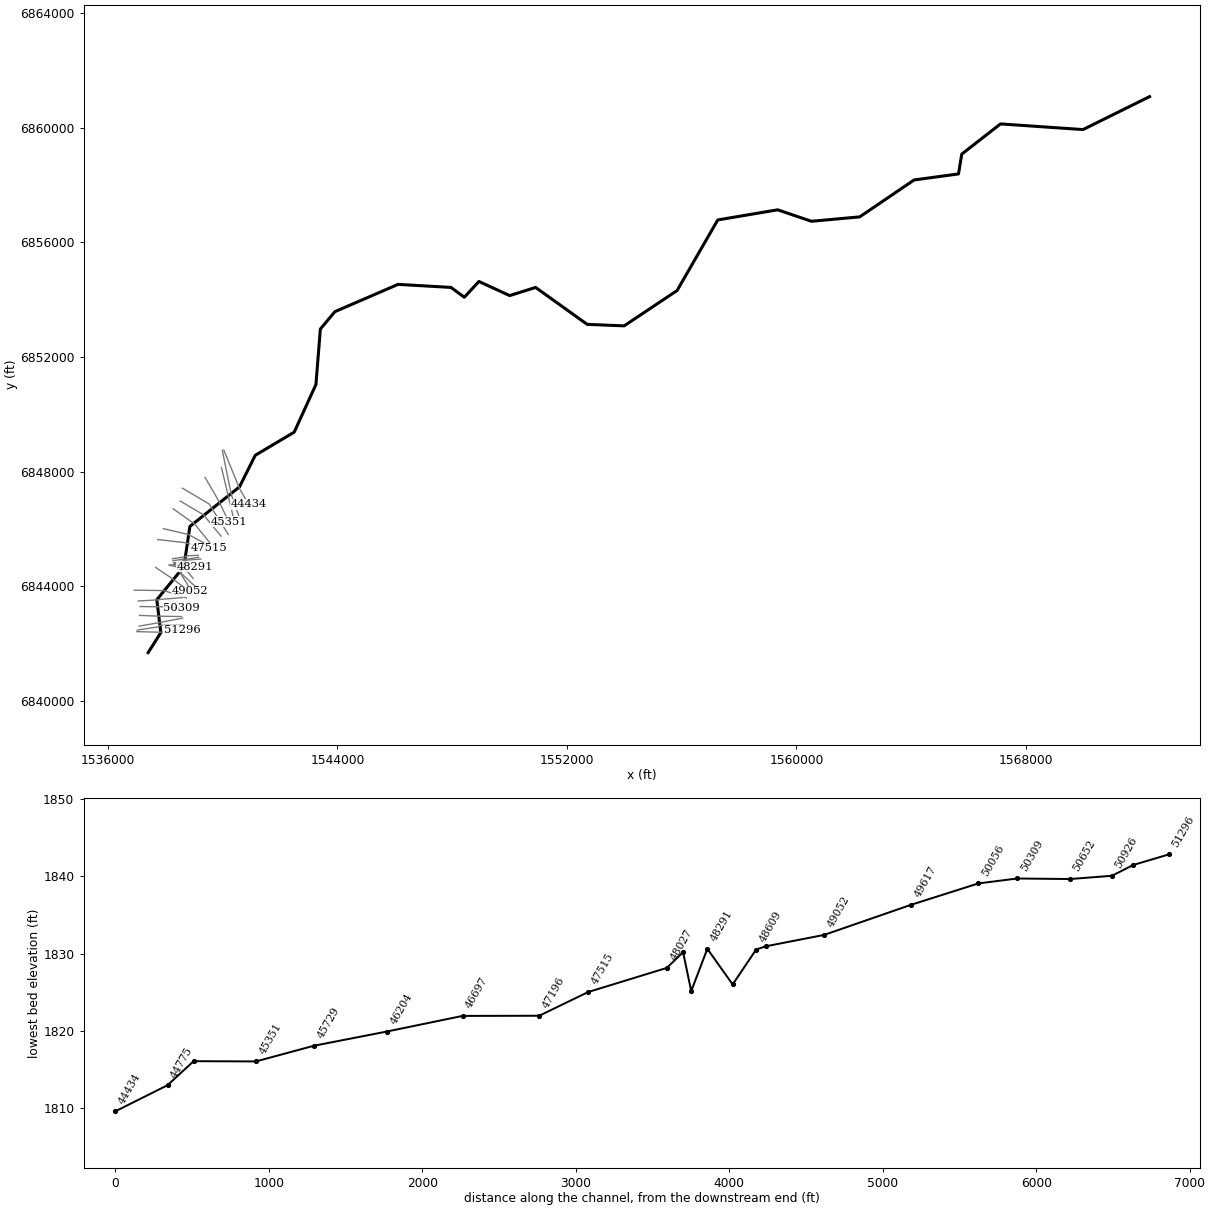
--- Indian Creek.prj (project) ---

Proj Title=Indian Creek Base Level Engineering
Current Plan=p01
Default Exp/Contr=0.3,0.1
English Units
Geom File=g01
Flow File=f01
Plan File=p01
Y Axis Title=Elevation
X Axis Title(PF)=Main Channel Distance
X Axis Title(XS)=Station
BEGIN DESCRIPTION:
Indian Creek
END DESCRIPTION:
DSS Export Rating Curves= 0
DSS Export Rating Curve Sorted= 0
DSS Export Volume Flow Curves= 0
DXF OffsetX= 0
DXF OffsetY= 0
DXF ScaleX= 1
DXF ScaleY= 10

--- Indian Creek.p01 (plan) ---

Plan Title=Multiple Run
Program Version=4.10
Short Identifier=Multiple
Geom File=g01
Flow File=f01
Subcritical Flow
K Sum by GR= 0
Std Step Tol= 0.01
Critical Tol= 0.01
Num of Std Step Trials= 20
Max Error Tol= 0.3
Flow Tol Ratio= 0.001
Split Flow NTrial= 30
Split Flow Tol= 0.02
Split Flow Ratio= 0.02
Log Output Level= 0
Friction Slope Method= 1
Unsteady Friction Slope Method= 2
Unsteady Bridges Friction Slope Method= 1
Parabolic Critical Depth
Global Vel Dist= 1 , 1 , 1
Global Log Level= 0
CheckData=True
Encroach Param=-1 ,0,0, 0
BEGIN DESCRIPTION:
Multiple Run
END DESCRIPTION:
Computation Interval=1HOUR
Output Interval=1HOUR
Run HTab= 0
Run UNet= 0
Run PostProcess= 0
Run WQNet= 0
UNET Theta= 1
UNET Theta Warmup= 1
UNET ZTol= 0.02
UNET ZSATol= 0.05
UNET MxIter= 20
UNET MaxInSteps= 0
UNET DtIC= 0
UNET DtMin= 0
UNET MaxCRTS= 20
UNET WFStab= 2
UNET SFStab= 1
UNET WFX= 1
UNET SFX= 1
UNET DSS MLevel= 4
UNET DZMax Abort= 100
UNET Convert EG Bridges= 0
UNET Use Existing IB Tables=-1
UNET Froude Reduction=False
UNET Froude Limit= 1
UNET Froude Power= 10
UNET Time Slicing=0,0, 5
UNET Junction Losses=0
Instantaneous Interval=1HOUR
Write IC File= 0
Write IC File at Sim End=0
Echo Input=False
Echo Parameters=False
Echo Output=False
Write Detailed= 0
WQ AD Non Conservative
WQ ULTIMATE=-1
WQ Max Comp Step=1HOUR
WQ Output Interval=15MIN
WQ Output Selected Increments= 0
WQ Output face flow=0
WQ Output face velocity=0
WQ Output face area=0
WQ Output face dispersion=0
WQ Output cell volume=0
WQ Output cell surface area=0
WQ Output cell continuity=0
WQ Output cumulative cell continuity=0
WQ Output face conc=0
WQ Output face dconc_dx=0
WQ Output face courant=0
WQ Output face peclet=0
WQ Output face adv mass=0
WQ Output face disp mass=0
WQ Output cell mass=0
WQ Output cell source sink temp=0
WQ Output cell source sink nsm=0
WQ Output MaxMinRange=-1
WQ Daily Max Min Mean=-1
WQ Daily Range=0
WQ Daily Time=0
WQ Create Restart=0
WQ Fixed Restart=0
WQ System Summary=0
WQ Use Fixed Temperature=0
Sorting and Armoring Iterations= 10
XS Update Threshold= 0.02
Hydraulics Update Threshold= 0.02
Energy Slope Method= 1
Volume Change Method= 0
XS Weighting Method= 0
Number of US Weighted Cross Sections= 1
Number of DS Weighted Cross Sections= 1
Upstream XS Weight=0.25
Main XS Weight=0.5
Downstream XS Weight=0.25
Number of DS XS's Weighted with US Boundary= 1
Upstream Boundary Weight= 1
Weight of XSs Associated with US Boundary= 0
Number of US XS's Weighted with DS Boundary= 1
Downstream Boundary Weight= 0.5
Weight of XSs Associated with DS Boundary= 0.5
Sediment Output Level= 4
Mass or Volume Output= 0
Output Increment Type= 1
Profile and TS Output Increment= 10
XS Output Flag= 0
XS Output Increment= 10
Disregard all LS=0
Disregard all Conn=0
Disregard all Breaches=0
Disregard all Pumps=0

--- Indian Creek.f01 (steady flow) ---

Flow Title=Multiple
Number of Profiles=7
Profile Names=10-year,25-year,50-year,1pct_min,100-year,1pct_plu,500-year
River Rch & RM= Indian Creek,Reach-1,51296
     260     357     436     330     529     727     787
River Rch & RM= Indian Creek,Reach-1,46204
     359     501     619     474     759    1040    1160
River Rch & RM= Indian Creek,Reach-1,41044
     458     648     808     622     997    1370    1540
River Rch & RM= Indian Creek,Reach-1,37285
     549     784     983     761    1220    1680    1910
River Rch & RM= Indian Creek,Reach-1,33551
     631     906    1140     887    1420    1960    2240
River Rch & RM= Indian Creek,Reach-1,29279
     691     996    1260     980    1570    2160    2480
River Rch & RM= Indian Creek,Reach-1,24516
     752    1090    1370    1070    1720    2370    2730
River Rch & RM= Indian Creek,Reach-1,19184
     831    1210    1530    1200    1920    2640    3060
River Rch & RM= Indian Creek,Reach-1,16431
     892    1300    1650    1290    2070    2840    3300
River Rch & RM= Indian Creek,Reach-1,10018
    1150    1690    2170    1710    2730    3760    4420
River Rch & RM= Indian Creek,Reach-1,7070
    1220    1790    2290    1800    2890    3970    4650
River Rch & RM= Indian Creek,Reach-1,1660
    1260    1840    2360    1860    2980    4090    4810
Boundary for River Rch & Prof#=Indian Creek,Reach-1,1
Up Type=0
Dn Type=3
Dn Slope=0.0002
Boundary for River Rch & Prof#=Indian Creek,Reach-1,2
Up Type=0
Dn Type=3
Dn Slope=0.0002
Boundary for River Rch & Prof#=Indian Creek,Reach-1,3
Up Type=0
Dn Type=3
Dn Slope=0.0002
Boundary for River Rch & Prof#=Indian Creek,Reach-1,4
Up Type=0
Dn Type=3
Dn Slope=0.0002
Boundary for River Rch & Prof#=Indian Creek,Reach-1,5
Up Type=0
Dn Type=3
Dn Slope=0.0002
Boundary for River Rch & Prof#=Indian Creek,Reach-1,6
Up Type=0
Dn Type=3
Dn Slope=0.0002
Boundary for River Rch & Prof#=Indian Creek,Reach-1,7
Up Type=0
Dn Type=3
Dn Slope=0.0002

--- Indian Creek.g01 (geometry) ---

Geom Title=Existing Conditions
Program Version=4.10

River Reach=Indian Creek    ,Reach-1
Reach XY= 30
        1537405.        6841688.      1537847.31      6842384.33
      1537707.07      6843532.53      1538651.46      6844689.47
      1538860.34      6846090.74      1540588.58       6847471.2
      1541137.87      6848571.97      1542496.82      6849381.96
      1543252.83      6851043.43      1543406.85      6852976.86
      1543913.16      6853584.62      1546114.65      6854536.64
      1547958.67      6854430.31      1548425.05      6854087.39
      1548932.24      6854638.29        1550005.      6854145.08
      1550908.42      6854430.21      1552706.47      6853141.54
       1553994.5      6853089.22      1555838.71      6854321.29
      1557256.68       6856784.9      1559344.83       6857138.5
      1560520.21      6856738.51      1562203.53      6856891.56
      1564098.92      6858179.91       1565647.1      6858390.91
      1565760.47      6859082.74      1567110.97      6860135.67
      1569984.97      6859938.04        1572305.        6861088.

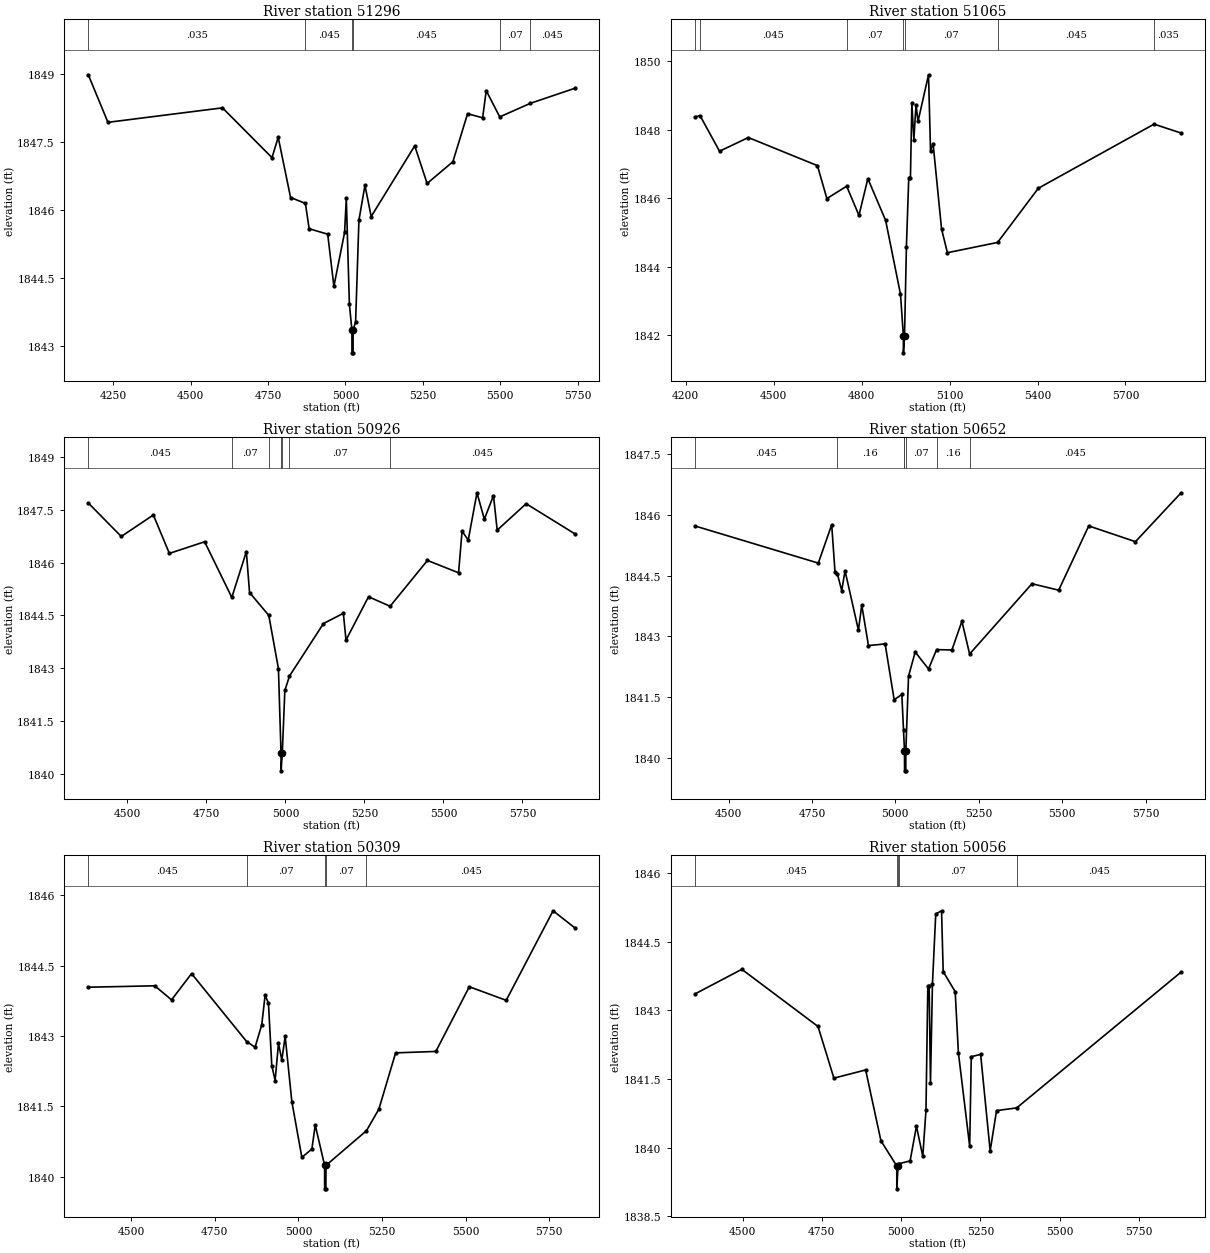
Type RM Length L Ch R = 1 ,51296   ,231,231,231
BEGIN DESCRIPTION:
Indian Creek 51295.72
END DESCRIPTION:
XS GIS Cut Line= 3
       1537011.5      6842419.73      1537839.59       6842398.9
      1538579.15      6842471.81
#Sta/Elev= 30
  4168.8 1848.99  4232.3 1847.94  4602.4 1848.26  4762.5 1847.16  4782.5 1847.61
  4822.5 1846.28  4870.4 1846.15  4882.5 1845.59  4942.5 1845.47  4962.5 1844.32
  4997.1 1845.51  5002.6 1846.26  5012.6 1843.92  5020.7 1843.35  5020.9 1842.85
  5024.4 1842.85  5024.7 1843.35  5032.7 1843.54  5043.4 1845.78  5062.9 1846.55
    5083 1845.86  5223.7 1847.42  5263.8 1846.59    5347 1847.07  5394.5 1848.13
  5443.2 1848.04  5454.8 1848.64  5498.4 1848.06  5597.6 1848.36  5740.3 1848.69
#Mann= 6 ,-1 , 0
  4168.8    .035       0  4870.4    .045       0  5020.7    .045       0
  5024.7    .045       0  5498.4     .07       0  5597.6    .045       0
Bank Sta=5020.7,5024.7
XS Rating Curve= 0 ,0
Exp/Cntr=0.3,0.1

Type RM Length L Ch R = 1 ,51065   ,139,139,139
BEGIN DESCRIPTION:
Indian Creek 18.0
END DESCRIPTION:
XS GIS Cut Line= 4
      1537031.69      6842474.87      1537755.67      6842586.45
      1537812.15      6842637.64      1538661.97      6842643.63
#Sta/Elev= 30
  4231.1 1848.37  4248.8 1848.41  4315.4 1847.37  4413.6 1847.77  4649.3 1846.95
  4681.5 1845.99    4749 1846.35  4790.9  1845.5  4821.3 1846.57    4882 1845.35
  4932.6  1843.2  4942.4 1841.99  4942.6 1841.49  4946.4 1841.99  4952.8 1844.59
  4960.8  1846.6  4966.5  1846.6  4971.4 1848.77  4978.2 1847.71  4985.6 1848.73
  4992.4 1848.24  5028.2  1849.6    5035 1847.39  5043.8 1847.59  5072.7  1845.1
  5092.7 1844.41  5263.8 1844.71  5402.7 1846.29  5797.4 1848.16  5889.7  1847.9
#Mann= 7 ,-1 , 0
  4231.1     .07       0  4248.8    .045       0    4749     .07       0
  4942.4     .07       0  4946.4     .07       0  5263.8    .045       0
  5797.4    .035       0
Bank Sta=4942.4,4946.4
XS Rating Curve= 0 ,0
Exp/Cntr=0.3,0.1

Type RM Length L Ch R = 1 ,50926   ,274,274,274
BEGIN DESCRIPTION:
Indian Creek 50913.12
END DESCRIPTION:
XS GIS Cut Line= 3
      1537092.24      6842612.58      1537669.24      6842712.26
      1538605.52      6842890.29
#Sta/Elev= 30
  4376.4 1847.69  4480.7 1846.74  4582.2 1847.35  4632.9 1846.26  4744.5 1846.59
  4830.5 1845.01  4876.5 1846.31  4886.6 1845.15  4947.5  1844.5    4978 1842.99
  4986.2 1840.59  4986.4 1840.09  4990.2 1840.59  4998.3 1842.37    5013 1842.78
  5120.5 1844.27  5183.4 1844.56  5191.8  1843.8    5263 1845.03  5331.3 1844.76
  5449.5 1846.06    5548 1845.71    5559 1846.89  5578.6 1846.64  5606.2 1847.98
  5629.5 1847.23  5658.4  1847.9  5670.2 1846.92  5761.8 1847.67    5915 1846.82
#Mann= 7 ,-1 , 0
  4376.4    .045       0  4830.5     .07       0  4947.5     .16       0
  4986.2     .07       0  4990.2     .16       0    5013     .07       0
  5331.3    .045       0
Bank Sta=4986.2,4990.2
XS Rating Curve= 0 ,0
Exp/Cntr=0.3,0.1

Type RM Length L Ch R = 1 ,50652   ,343,343,343
BEGIN DESCRIPTION:
Indian Creek 50652.24
END DESCRIPTION:
XS GIS Cut Line= 3
      1537105.21      6842987.44      1537704.17       6842961.4
       1538561.8      6842945.81
#Sta/Elev= 30
    4399 1845.73  4769.1 1844.81  4809.2 1845.76  4819.2 1844.58    4826 1844.55
  4839.2 1844.13  4849.2 1844.62  4889.3 1843.15  4899.3 1843.77  4919.3 1842.77
  4969.3 1842.81  4996.4 1841.43  5019.4 1841.56  5024.4 1840.68  5027.3 1840.17
  5027.6 1839.67  5031.2 1839.67  5031.4 1840.17  5039.4 1842.01  5059.4 1842.61
  5099.4 1842.19  5123.5 1842.67  5169.4 1842.66  5199.4 1843.37  5222.5 1842.56
  5409.4  1844.3  5489.4 1844.14  5579.5 1845.73  5719.5 1845.34  5856.3 1846.55
#Mann= 7 ,-1 , 0
    4399    .045       0    4826     .16       0  5024.4     .07       0
  5027.3     .07       0  5031.4     .07       0  5123.5     .16       0
  5222.5    .045       0
Bank Sta=5027.3,5031.4
XS Rating Curve= 0 ,0
Exp/Cntr=0.3,0.1

Type RM Length L Ch R = 1 ,50309   ,253,253,253
BEGIN DESCRIPTION:
Indian Creek 50287.88
END DESCRIPTION:
XS GIS Cut Line= 3
      1537126.02      6843294.73      1537844.29      6843288.24
      1538579.14      6843237.44
#Sta/Elev= 30
  4371.3 1844.04  4570.3 1844.07  4620.3 1843.77  4680.3 1844.33  4845.2 1842.88
  4870.3 1842.76  4890.3 1843.24  4900.3 1843.87  4910.3  1843.7  4920.3 1842.37
  4930.3 1842.05  4940.3 1842.84  4950.3 1842.49  4960.3 1842.99  4980.3  1841.6
  5010.3 1840.41  5040.3 1840.59  5050.3  1841.1  5078.3 1840.24  5078.5 1839.74
  5082.1 1839.74  5082.4 1840.24  5203.6 1840.98  5240.7 1841.44  5290.8 1842.64
  5411.1 1842.67  5511.3 1844.05  5621.6 1843.76  5761.9 1845.67  5826.2 1845.31
#Mann= 5 ,-1 , 0
  4371.3    .045       0  4845.2     .07       0  5078.3     .07       0
  5082.4     .07       0  5203.6    .045       0
Bank Sta=5078.3,5082.4
XS Rating Curve= 0 ,0
Exp/Cntr=0.3,0.1

Type RM Length L Ch R = 1 ,50056   ,439,439,439
BEGIN DESCRIPTION:
Indian Creek 49837.92
END DESCRIPTION:
XS GIS Cut Line= 4
      1537056.95      6843489.17      1537791.72      6843531.34
      1537853.61      6843547.83      1538585.63      6843603.91
#Sta/Elev= 30
  4349.2 1843.36  4497.5  1843.9  4737.9 1842.65    4788 1841.52  4888.1  1841.7
  4936.4 1840.15  4986.3  1839.6  4986.5  1839.1  4990.4  1839.6  4993.2 1839.65
  5028.4 1839.71  5048.4 1840.47  5068.4 1839.81  5078.5 1840.82  5084.3 1843.54
  5088.4 1843.54  5092.7 1841.42  5098.9 1843.58  5109.3 1845.11  5127.6 1845.18
  5132.8 1843.85  5170.7 1843.41  5180.7 1842.08  5216.4 1840.03  5221.4 1841.99
  5250.9 1842.04    5281 1839.93  5301.1 1840.81  5364.7 1840.87  5883.4 1843.84
#Mann= 5 ,-1 , 0
  4349.2    .045       0  4986.3     .07       0  4990.4    .045       0
  4993.2     .07       0  5364.7    .045       0
Bank Sta=4986.3,4990.4
XS Rating Curve= 0 ,0
Exp/Cntr=0.3,0.1

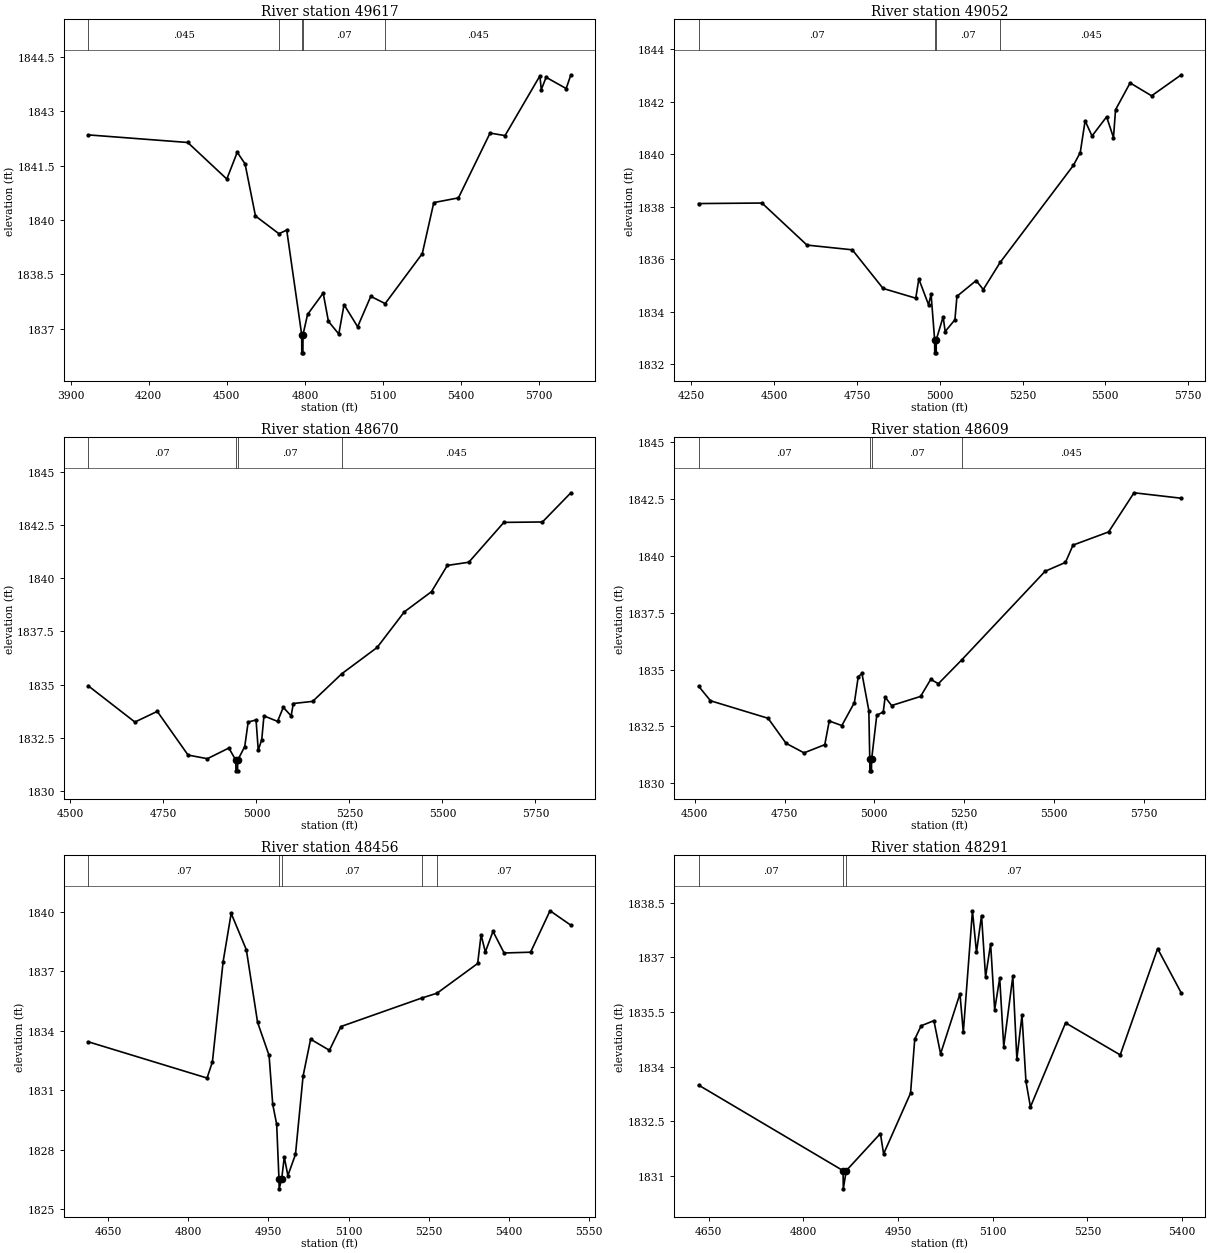
Type RM Length L Ch R = 1 ,49617   ,565,565,565
BEGIN DESCRIPTION:
Indian Creek 49617.05
END DESCRIPTION:
XS GIS Cut Line= 3
      1536922.96      6843867.65      1537954.17      6843852.02
      1538735.41      6843596.82
#Sta/Elev= 30
  3967.9 1842.35    4350 1842.14    4500 1841.13    4540 1841.87    4570 1841.55
    4610 1840.11  4700.1 1839.62    4730 1839.72  4787.5 1836.83  4787.9 1836.33
  4792.1 1836.33  4792.5 1836.83    4810 1837.39    4870 1837.98  4890.1  1837.2
  4929.9 1836.85  4950.1 1837.66  5002.3 1837.05  5052.7 1837.89    5108 1837.69
  5250.5 1839.07  5294.7 1840.48  5389.3 1840.61  5510.8  1842.4  5568.2 1842.33
  5702.1 1843.98  5707.4  1843.6    5726 1843.94    5803 1843.63  5821.1 1844.01
#Mann= 5 ,-1 , 0
  3967.9    .045       0  4700.1     .07       0  4787.5     .07       0
  4792.5     .07       0    5108    .045       0
Bank Sta=4787.5,4792.5
XS Rating Curve= 0 ,0
Exp/Cntr=0.3,0.1

Type RM Length L Ch R = 1 ,49052   ,382,382,382
BEGIN DESCRIPTION:
Indian Creek 49267.05
END DESCRIPTION:
XS GIS Cut Line= 3
       1537663.5      6844661.24      1538205.17      6844296.66
      1538856.03      6843822.83
#Sta/Elev= 30
  4271.6 1838.12  4462.8 1838.14  4598.9 1836.54  4735.8 1836.36  4828.8 1834.89
  4927.5 1834.52  4936.8 1835.25  4966.2 1834.27  4973.8 1834.67  4984.5 1832.94
  4984.9 1832.44  4989.2 1832.44  4989.5 1832.94  5010.2 1833.81  5016.4 1833.25
  5045.8  1833.7  5051.9 1834.59  5109.9 1835.19  5131.5 1834.85  5182.4 1835.88
  5403.5 1839.57  5424.4 1840.06  5439.1 1841.27  5459.9 1840.69    5504 1841.42
  5524.8 1840.63    5531 1841.69    5575 1842.71    5640 1842.22  5729.6 1843.02
#Mann= 4 ,-1 , 0
  4271.6     .07       0  4984.5     .07       0  4989.5     .07       0
  5182.4    .045       0
Bank Sta=4984.5,4989.5
XS Rating Curve= 0 ,0
Exp/Cntr=0.3,0.1

Type RM Length L Ch R = 1 ,48670   ,61,61,61
BEGIN DESCRIPTION:
Indian Creek 48865.3
END DESCRIPTION:
XS GIS Cut Line= 3
      1538133.72      6844738.82      1538388.49      6844683.49
      1538938.56      6843805.12
#Sta/Elev= 30
  4548.1 1834.95  4673.5 1833.25  4733.6 1833.75  4816.4  1831.7  4868.3 1831.53
    4926 1832.03  4944.7 1831.46  4945.1 1830.96  4949.4 1830.96  4949.8 1831.46
  4968.7  1832.1  4977.9 1833.25  4999.1 1833.35    5005 1831.93  5014.4 1832.42
  5020.3 1833.54  5056.9 1833.28  5072.2 1833.94  5093.4 1833.54  5099.3 1834.12
  5151.2 1834.22  5229.7 1835.52  5324.5 1836.75  5397.5 1838.42  5470.6 1839.37
  5513.1  1840.6  5570.8 1840.75  5665.1 1842.62  5768.8 1842.64  5845.2 1844.01
#Mann= 4 ,-1 , 0
  4548.1     .07       0  4944.7     .07       0  4949.8     .07       0
  5229.7    .045       0
Bank Sta=4944.7,4949.8
XS Rating Curve= 0 ,0
Exp/Cntr=0.3,0.1

Type RM Length L Ch R = 1 ,48609   ,153,153,153
BEGIN DESCRIPTION:
Indian Creek 48593.65
END DESCRIPTION:
XS GIS Cut Line= 4
      1538172.05      6844752.16      1538488.97      6844730.63
      1538564.47      6844445.67       1539100.6      6843947.34
#Sta/Elev= 30
  4510.7 1834.27  4543.7 1833.63  4704.1 1832.86  4754.2 1831.76  4804.3 1831.34
  4862.1  1831.7  4874.5 1832.74  4909.6 1832.54  4944.6 1833.55  4955.2 1834.68
  4965.6 1834.83  4984.8  1833.2  4987.4 1831.05  4987.8 1830.55  4992.1 1830.55
  4992.5 1831.05  5006.9 1832.99    5025 1833.14  5030.2 1833.79  5048.3 1833.42
  5128.9 1833.82  5157.2 1834.57  5178.5 1834.38  5243.2 1835.42  5475.8 1839.32
  5532.5 1839.71  5553.5 1840.47  5652.7 1841.05  5723.5 1842.77  5855.1 1842.53
#Mann= 4 ,-1 , 0
  4510.7     .07       0  4987.4     .07       0  4992.5     .07       0
  5243.2    .045       0
Bank Sta=4987.4,4992.5
XS Rating Curve= 0 ,0
Exp/Cntr=0.3,0.1

Type RM Length L Ch R = 1 ,48456   ,165,165,165
BEGIN DESCRIPTION:
Indian Creek 16.0
END DESCRIPTION:
XS GIS Cut Line= 4
      1538292.79      6844771.33      1538556.96      6844764.36
      1538704.59      6844603.11      1538970.25      6844277.78
#Sta/Elev= 30
    4613 1833.45  4835.3 1831.62  4845.3 1832.44  4865.3 1837.49  4880.4 1839.93
  4908.8 1838.09  4929.8 1834.43  4951.3 1832.76  4958.1  1830.3  4965.5 1829.29
  4969.8 1826.53  4970.2 1826.03  4974.9 1826.53  4979.7 1827.63  4986.5  1826.7
  5000.7 1827.77  5014.9 1831.72    5029 1833.58  5064.2 1833.02  5085.8 1834.22
  5237.1 1835.66  5265.4  1835.9  5341.5  1837.4  5347.9 1838.85  5355.8 1837.98
  5370.2 1839.02    5391 1837.93  5440.5 1837.97  5476.9 1840.06  5515.9 1839.33
#Mann= 5 ,-1 , 0
    4613     .07       0  4969.8     .07       0  4974.9     .07       0
  5237.1    .045       0  5265.4     .07       0
Bank Sta=4969.8,4974.9
XS Rating Curve= 0 ,0
Exp/Cntr=0.3,0.1

Type RM Length L Ch R = 1 ,48291   ,105,105,105
BEGIN DESCRIPTION:
Indian Creek 14.0
END DESCRIPTION:
XS GIS Cut Line= 5
      1538295.92      6844792.06      1538628.43       6844839.6
       1538701.7      6844828.24      1538794.69      6844754.28
      1539019.81      6844682.95
#Sta/Elev= 30
  4633.9 1833.49  4862.8 1831.14  4863.2 1830.64  4867.9 1831.14    4922 1832.16
  4927.1  1831.6  4969.8 1833.27  4976.4 1834.75  4986.6 1835.12  5006.8 1835.26
  5017.4 1834.35  5048.1    1836  5053.4 1834.94  5067.9 1838.28  5074.3 1837.14
  5082.3 1838.15  5088.7 1836.46  5096.7 1837.37  5103.1 1835.56  5111.1 1836.43
  5117.5 1834.55  5131.9 1836.48  5138.3 1834.21  5146.4 1835.41  5152.7 1833.59
  5159.8 1832.89  5215.5  1835.2  5302.1 1834.32  5361.4 1837.24  5398.9 1836.02
#Mann= 3 ,-1 , 0
  4633.9     .07       0  4862.8     .07       0  4867.9     .07       0
Bank Sta=4862.8,4867.9
XS Rating Curve= 0 ,0
Exp/Cntr=0.3,0.1

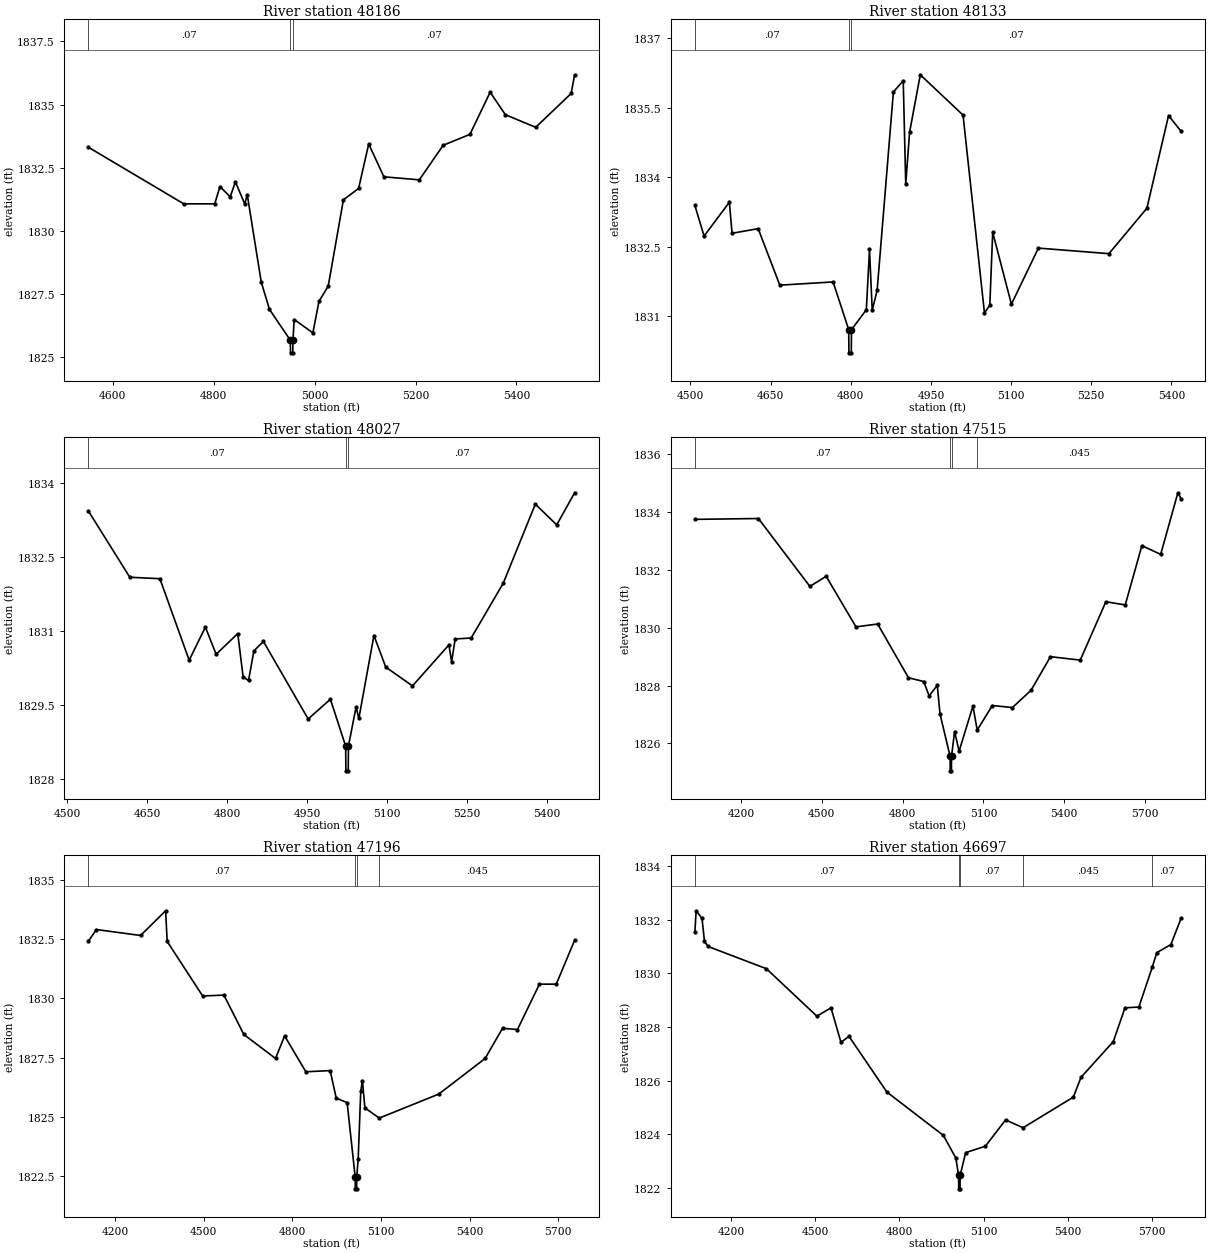
Type RM Length L Ch R = 1 ,48186   ,53,53,53
BEGIN DESCRIPTION:
Indian Creek 48186.27
END DESCRIPTION:
XS GIS Cut Line= 3
       1538290.4      6844816.38      1538740.63      6844914.52
      1539241.89      6844952.51
#Sta/Elev= 30
  4551.8 1833.31  4740.7 1831.07  4802.1 1831.07  4812.4 1831.75  4832.8 1831.35
  4843.1 1831.94  4861.5 1831.07  4866.6 1831.43  4894.3 1827.97  4910.6 1826.89
  4951.9 1825.67  4952.3 1825.17  4956.7 1825.17  4957.1 1825.67  4959.6 1826.49
  4996.6 1825.96  5008.7 1827.21    5027 1827.81  5057.1 1831.23  5087.2 1831.68
  5107.2 1833.44  5137.3 1832.14  5207.5 1832.02  5254.9 1833.39  5307.8 1833.82
  5347.9 1835.49    5378  1834.6  5438.2  1834.1  5508.4 1835.44  5515.3 1836.18
#Mann= 3 ,-1 , 0
  4551.8     .07       0  4951.9     .07       0  4957.1     .07       0
Bank Sta=4951.9,4957.1
XS Rating Curve= 0 ,0
Exp/Cntr=0.3,0.1

Type RM Length L Ch R = 1 ,48133   ,106,106,106
BEGIN DESCRIPTION:
Indian Creek 13.0
END DESCRIPTION:
XS GIS Cut Line= 4
      1538267.97      6844892.87      1538659.31      6844953.46
      1538820.89      6844958.25      1539168.17      6845015.98
#Sta/Elev= 30
  4508.3 1833.39  4525.5 1832.73  4572.8 1833.46  4577.9 1832.79  4626.7 1832.89
  4667.2 1831.67  4766.9 1831.74  4796.1 1830.71  4796.5 1830.21  4800.9 1830.21
  4801.3 1830.71  4829.1 1831.14    4835 1832.44  4840.1 1831.13  4849.3 1831.56
  4879.7 1835.84  4898.1 1836.08  4902.8 1833.85    4910 1834.97    4930 1836.21
    5010 1835.34  5050.1 1831.07  5060.1 1831.24  5065.5 1832.81  5100.5 1831.26
    5151 1832.47    5283 1832.35    5354 1833.33  5394.5 1835.33    5418 1834.99
#Mann= 3 ,-1 , 0
  4508.3     .07       0  4796.1     .07       0  4801.3     .07       0
Bank Sta=4796.1,4801.3
XS Rating Curve= 0 ,0
Exp/Cntr=0.3,0.1

Type RM Length L Ch R = 1 ,48027   ,512,512,512
BEGIN DESCRIPTION:
Indian Creek 47903.49
END DESCRIPTION:
XS GIS Cut Line= 4
      1538248.32      6844962.38      1538639.68      6845022.98
      1538787.08      6845066.05      1539148.57       6845085.5
#Sta/Elev= 30
  4539.8 1833.43  4617.4 1832.09  4673.8 1832.06  4728.7 1830.41  4759.1 1831.08
  4779.3 1830.53  4819.8 1830.95  4829.9 1830.07    4840    1830  4850.1  1830.6
  4867.9 1830.79  4951.8 1829.22  4993.5 1829.62  5022.1 1828.67  5022.5 1828.17
  5026.9 1828.17  5027.3 1828.67  5041.6 1829.46  5046.8 1829.23  5075.1 1830.91
  5097.3 1830.27  5147.4 1829.89  5215.7 1830.72  5220.7 1830.38  5227.5 1830.84
  5257.5 1830.86  5317.6 1831.97  5377.7 1833.57  5417.8 1833.15  5451.4  1833.8
#Mann= 3 ,-1 , 0
  4539.8     .07       0  5022.1     .07       0  5027.3     .07       0
Bank Sta=5022.1,5027.3
XS Rating Curve= 0 ,0
Exp/Cntr=0.3,0.1

Type RM Length L Ch R = 1 ,47515   ,319,319,319
BEGIN DESCRIPTION:
Indian Creek 47515.24
END DESCRIPTION:
XS GIS Cut Line= 3
      1537740.65      6845633.27      1538693.75       6845523.9
      1539516.63      6845325.99
#Sta/Elev= 30
  4028.4 1833.75  4264.3 1833.78  4455.5 1831.43  4515.9 1831.78  4626.7 1830.03
  4707.2 1830.13  4821.6 1828.27  4878.3 1828.14  4898.4 1827.64  4928.6 1828.01
  4938.7 1827.02  4976.3 1825.55  4976.7 1825.05  4981.1 1825.05  4981.5 1825.55
  4992.9 1826.41  5009.6 1825.73    5061 1827.29  5076.9 1826.46    5133 1827.31
  5207.8 1827.24    5277 1827.84    5349    1829  5459.5 1828.88  5554.7  1830.9
  5626.7 1830.79  5688.4 1832.84  5758.3 1832.54  5822.1 1834.67  5834.1 1834.46
#Mann= 4 ,-1 , 0
  4028.4     .07       0  4976.3     .07       0  4981.5     .07       0
  5076.9    .045       0
Bank Sta=4976.3,4981.5
XS Rating Curve= 0 ,0
Exp/Cntr=0.3,0.1

Type RM Length L Ch R = 1 ,47196   ,499,499,499
BEGIN DESCRIPTION:
Indian Creek 47196.1
END DESCRIPTION:
XS GIS Cut Line= 3
      1537938.58      6846013.47      1538803.13      6845810.36
      1539469.84      6845450.96
#Sta/Elev= 30
  4109.8 1832.41  4136.9  1832.9  4286.3 1832.65  4371.1 1833.69  4376.3  1832.4
  4496.5  1830.1  4568.4 1830.14  4635.8 1828.48    4743 1827.47  4773.8 1828.42
  4845.7 1826.91  4927.9 1826.96  4948.5  1825.8  4985.4 1825.61  5012.6 1822.48
    5013 1821.98  5017.5 1821.98  5017.9 1822.48  5022.7 1823.22  5031.4 1826.08
  5037.1 1826.54  5045.5 1825.39  5094.1 1824.96  5295.4 1825.97  5452.4 1827.47
  5511.2 1828.74  5561.8 1828.69  5636.2  1830.6  5693.2  1830.6  5755.3 1832.45
#Mann= 4 ,-1 , 0
  4109.8     .07       0  5012.6     .07       0  5017.9     .07       0
  5094.1    .045       0
Bank Sta=5012.6,5017.9
XS Rating Curve= 0 ,0
Exp/Cntr=0.3,0.1

Type RM Length L Ch R = 1 ,46697   ,493,493,493
BEGIN DESCRIPTION:
Indian Creek 46696.85
END DESCRIPTION:
XS GIS Cut Line= 3
      1538277.11      6846706.18       1539032.3      6846169.73
      1539537.48      6845539.56
#Sta/Elev= 30
  4070.4 1831.55  4074.9 1832.33  4095.8 1832.05  4104.5  1831.2  4116.9    1831
  4325.4 1830.17  4505.4  1828.4  4555.9 1828.71  4591.5 1827.42  4619.8 1827.65
  4755.1 1825.57  4956.8 1823.95    5001 1823.11  5010.9 1822.46  5011.3 1821.96
  5015.9 1821.96  5016.4 1822.46    5036 1823.31  5106.4 1823.55  5178.4 1824.53
  5240.9 1824.24  5420.1 1825.38  5447.5 1826.12  5562.5 1827.45  5604.2 1828.71
  5653.8 1828.74  5701.7 1830.23  5717.8 1830.77  5767.9 1831.07  5804.4 1832.05
#Mann= 5 ,-1 , 0
  4070.4     .07       0  5010.9     .07       0  5016.4     .07       0
  5240.9    .045       0  5701.7     .07       0
Bank Sta=5010.9,5016.4
XS Rating Curve= 0 ,0
Exp/Cntr=0.3,0.1

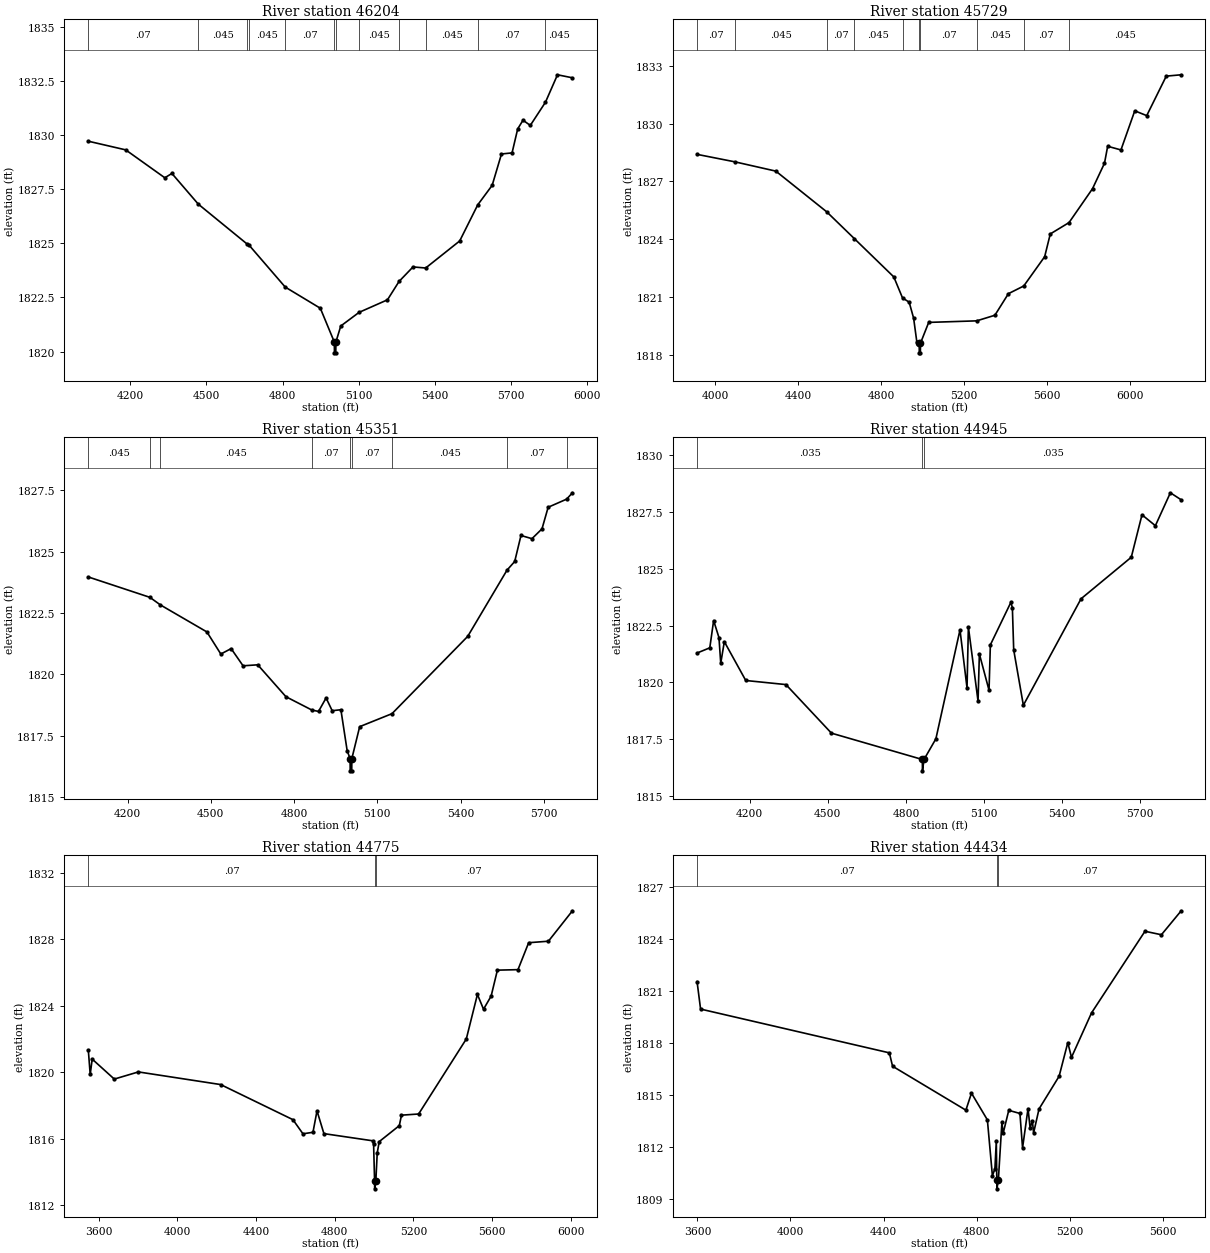
Type RM Length L Ch R = 1 ,46204   ,475,475,475
BEGIN DESCRIPTION:
Indian Creek 46203.72
END DESCRIPTION:
XS GIS Cut Line= 3
      1538521.89      6846977.01      1539339.59      6846492.65
      1539943.77      6845753.04
#Sta/Elev= 30
  4035.5 1829.72  4182.6 1829.32  4336.6 1828.03  4364.5 1828.23  4468.5 1826.81
  4659.3 1824.98  4667.9 1824.92  4810.4 1822.98  4948.7    1822  5003.7 1820.44
  5004.2 1819.94  5009.4 1819.94  5009.9 1820.44  5029.1 1821.18  5101.1 1821.81
  5212.8 1822.39  5258.5 1823.24  5313.4 1823.91  5363.2 1823.86  5497.1 1825.11
  5568.2 1826.78  5624.9 1827.68  5661.6 1829.13  5703.2 1829.18  5725.4 1830.29
  5746.3 1830.69    5775 1830.45  5834.6 1831.52    5882 1832.79  5940.9 1832.65
#Mann= 12 ,-1 , 0
  4035.5     .07       0  4468.5    .045       0  4659.3     .07       0
  4667.9    .045       0  4810.4     .07       0  5003.7     .07       0
  5009.9     .07       0  5101.1    .045       0  5258.5     .07       0
  5363.2    .045       0  5568.2     .07       0  5834.6    .045       0
Bank Sta=5003.7,5009.9
XS Rating Curve= 0 ,0
Exp/Cntr=0.3,0.1

Type RM Length L Ch R = 1 ,45729   ,378,378,378
BEGIN DESCRIPTION:
Indian Creek 45728.78
END DESCRIPTION:
XS GIS Cut Line= 3
      1538600.01      6847424.94       1539532.3      6846872.86
      1540198.15      6845811.65
#Sta/Elev= 30
  3911.1  1828.4  4094.4 1828.01  4291.2 1827.53  4536.5 1825.42  4669.8 1824.03
  4860.5 1822.04  4902.5 1820.95  4934.6 1820.73  4956.1  1819.9  4971.7 1818.66
    4983  1818.6  4983.5  1818.1  4988.7  1818.1  4989.2  1818.6  5028.9 1819.68
  5260.4 1819.76  5348.2 1820.05  5413.5 1821.17  5487.6 1821.57  5588.5 1823.09
  5615.6 1824.27  5706.1 1824.86  5819.5 1826.62  5877.2 1827.94  5892.5 1828.82
  5956.6 1828.63  6023.3 1830.66    6081 1830.41  6175.3 1832.46  6247.4 1832.53
#Mann= 10 ,-1 , 0
  3911.1     .07       0  4094.4    .045       0  4536.5     .07       0
  4669.8    .045       0  4902.5     .07       0    4983     .07       0
  4989.2     .07       0  5260.4    .045       0  5487.6     .07       0
  5706.1    .045       0
Bank Sta=4983,4989.2
XS Rating Curve= 0 ,0
Exp/Cntr=0.3,0.1

Type RM Length L Ch R = 1 ,45351   ,406,406,406
BEGIN DESCRIPTION:
Indian Creek 45445.31
END DESCRIPTION:
XS GIS Cut Line= 3
      1539390.03      6847797.18      1539846.56      6847015.48
      1540212.44      6846259.18
#Sta/Elev= 30
  4058.2 1823.97  4280.1 1823.14  4318.2 1822.83  4485.7 1821.73  4535.9 1820.83
  4573.1 1821.05  4616.1 1820.35    4669 1820.39  4770.7 1819.09  4863.7 1818.55
  4888.1 1818.49  4915.4 1819.04  4937.4 1818.52  4968.8 1818.56  4991.4 1816.89
  5001.9 1816.57  5002.4 1816.07  5007.8 1816.07  5008.3 1816.57  5036.5 1817.87
  5153.1  1818.4  5426.1 1821.55  5567.8 1824.25  5595.4  1824.6    5618 1825.66
  5657.6 1825.53  5693.8 1825.93    5716 1826.81  5782.5 1827.14  5803.6  1827.4
#Mann= 9 ,-1 , 0
  4058.2    .045       0  4280.1     .07       0  4318.2    .045       0
  4863.7     .07       0  5001.9     .07       0  5008.3     .07       0
  5153.1    .045       0  5567.8     .07       0  5782.5    .045       0
Bank Sta=5001.9,5008.3
XS Rating Curve= 0 ,0
Exp/Cntr=0.3,0.1

Type RM Length L Ch R = 1 ,44945   ,170,170,170
BEGIN DESCRIPTION:
Indian Creek 45105.03
END DESCRIPTION:
XS GIS Cut Line= 3
      1539958.46      6848149.83      1540183.86       6847208.4
      1540389.33      6846341.46
#Sta/Elev= 30
    3998 1821.29  4046.9 1821.52  4061.6 1822.72  4082.1 1821.97  4088.9 1820.84
  4102.7 1821.79    4185 1820.08  4339.2  1819.9    4514 1817.76    4863  1816.6
  4863.5  1816.1  4869.4  1816.6    4915 1817.51  5007.6 1822.31  5034.6 1819.75
  5039.8 1822.44  5076.9 1819.17    5082 1821.25  5119.1 1819.65  5124.2 1821.65
  5202.8 1823.52  5208.7 1823.29  5213.8 1821.43  5250.9 1818.99  5472.4 1823.68
  5665.3 1825.51  5706.4 1827.38  5757.8  1826.9  5815.4 1828.35    5857 1828.04
#Mann= 3 ,-1 , 0
    3998    .035       0    4863    .035       0  4869.4    .035       0
Bank Sta=4863,4869.4
XS Rating Curve= 0 ,0
Exp/Cntr=0.3,0.1

Type RM Length L Ch R = 1 ,44775   ,341,341,341
BEGIN DESCRIPTION:
Indian Creek 44719.24
END DESCRIPTION:
XS GIS Cut Line= 3
      1539990.63      6848737.42      1540304.33      6847199.92
       1540600.6      6846357.89
#Sta/Elev= 30
  3546.8 1821.34  3556.4 1819.87  3566.6 1820.79  3678.9 1819.59  3801.4 1820.02
  4219.8 1819.26  4587.2 1817.15  4638.2  1816.3  4689.1 1816.39  4709.7 1817.68
  4744.8 1816.31  4992.3 1815.88  4997.4 1815.69  5002.4 1813.49  5002.9 1812.99
  5008.9 1813.49  5015.9 1815.15  5026.1 1815.83  5128.2 1816.79  5139.2 1817.42
  5226.4 1817.49  5468.8    1822  5525.4 1824.68  5556.4 1823.79  5595.1 1824.58
  5626.9 1826.14  5731.6 1826.17  5785.9 1827.79  5886.4 1827.88  6008.6 1829.71
#Mann= 3 ,-1 , 0
  3546.8     .07       0  5002.4     .07       0  5008.9     .07       0
Bank Sta=5002.4,5008.9
XS Rating Curve= 0 ,0
Exp/Cntr=0.3,0.1

Type RM Length L Ch R = 1 ,44434   ,483,483,483
BEGIN DESCRIPTION:
Indian Creek 44195.32
END DESCRIPTION:
XS GIS Cut Line= 3
      1540042.72      6848753.06      1540597.45      6847396.86
      1540904.61      6846862.98
#Sta/Elev= 30
  3598.5 1821.53  3613.6 1819.95  4425.1 1817.43  4438.9 1816.66  4754.1 1814.13
  4778.1 1815.11  4846.5 1813.57  4868.1 1810.35  4878.9 1810.76  4884.9 1812.37
    4887  1810.1  4887.5  1809.6  4893.6  1810.1  4908.9 1813.42  4914.3  1812.8
  4938.4 1814.12  4986.4 1813.94  4997.7 1811.96  5021.2 1814.22  5030.1 1813.11
  5039.8 1813.51  5045.2 1812.82  5068.5  1814.2  5154.8 1816.08  5192.2 1818.02
    5208 1817.17  5294.2 1819.73  5523.9 1824.43  5594.6 1824.23  5679.7 1825.61
#Mann= 3 ,-1 , 0
  3598.5     .07       0    4887     .07       0  4893.6     .07       0
Bank Sta=4887,4893.6
XS Rating Curve= 0 ,0
Exp/Cntr=0.3,0.1