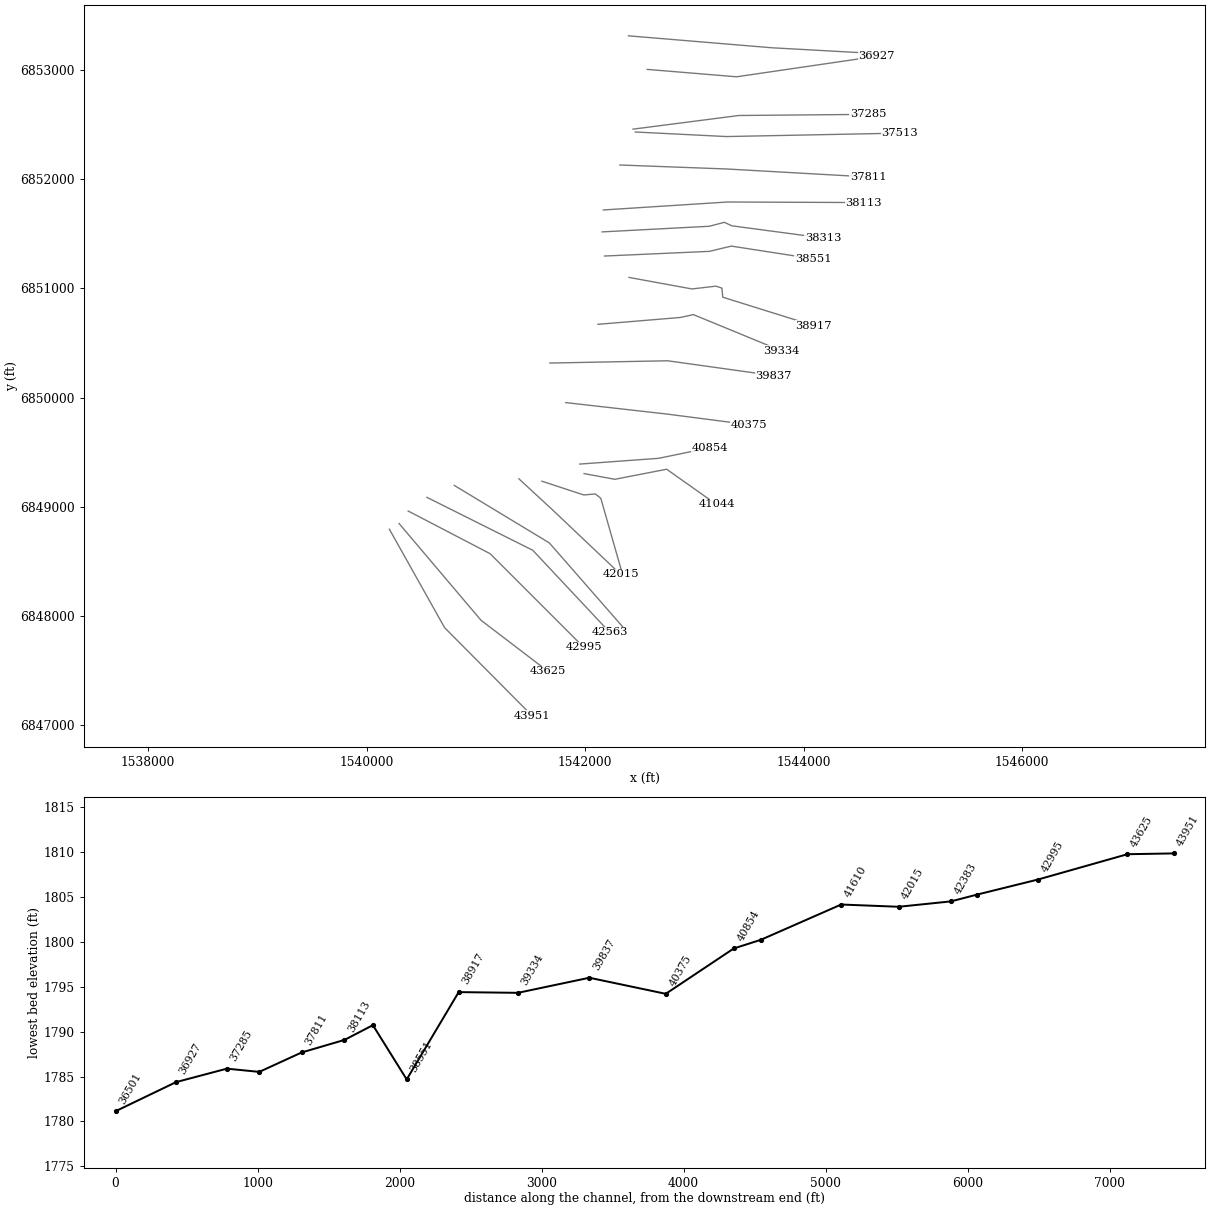
HEC-RAS study Indian Creek.prj: Indian Creek Base Level Engineering

--- Indian Creek.g01 (geometry) --- (continued)

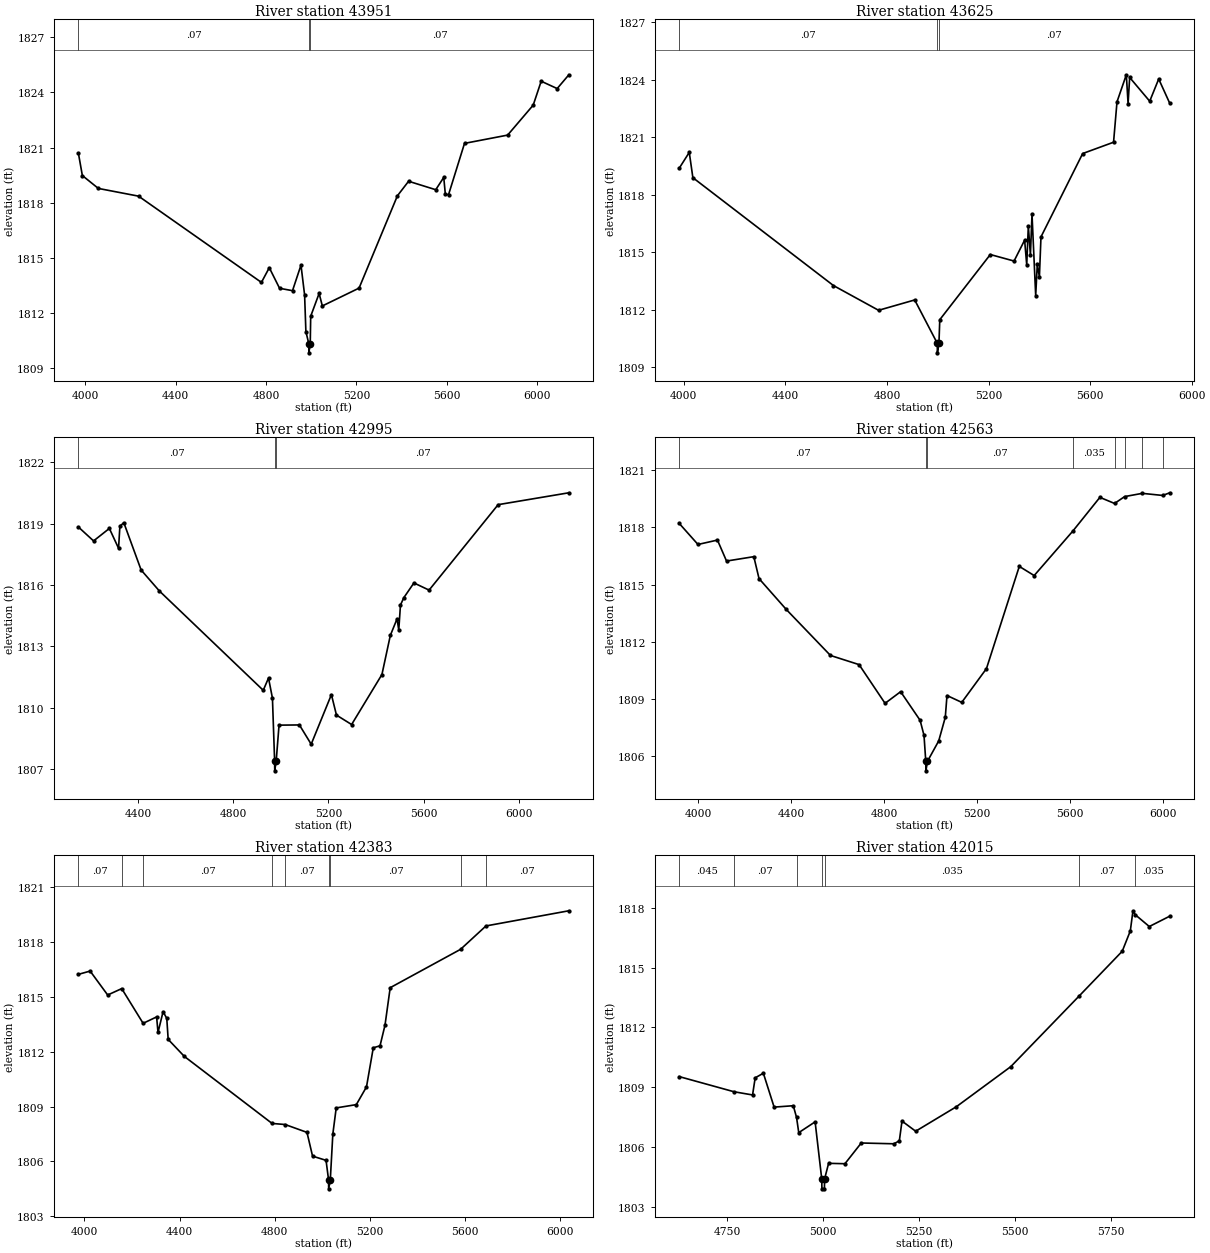
Type RM Length L Ch R = 1 ,43951   ,326,326,326
BEGIN DESCRIPTION:
Indian Creek 43951.44
END DESCRIPTION:
XS GIS Cut Line= 3
      1540209.38      6848794.74      1540714.59      6847893.69
      1541516.65      6847086.41
#Sta/Elev= 30
    3969  1820.7  3986.6 1819.48  4057.4 1818.78  4235.4 1818.36  4779.2 1813.67
    4814 1814.47  4859.5 1813.35  4916.8 1813.22  4954.3 1814.61  4970.3 1812.99
    4976    1811  4988.7 1810.34  4989.2 1809.84  4995.3 1810.34  4997.3 1811.83
  5034.6 1813.07  5048.8 1812.39  5211.4 1813.36  5381.1 1818.38  5430.6 1819.17
  5550.8 1818.71  5586.2 1819.38  5593.2 1818.47  5607.4 1818.44  5678.1 1821.23
    5869 1821.68  5982.2 1823.31  6017.5 1824.61  6088.2 1824.21    6140 1824.96
#Mann= 3 ,-1 , 0
    3969     .07       0  4988.7     .07       0  4995.3     .07       0
Bank Sta=4988.7,4995.3
XS Rating Curve= 0 ,0
Exp/Cntr=0.3,0.1

Type RM Length L Ch R = 1 ,43625   ,630,630,630
BEGIN DESCRIPTION:
Indian Creek 43625.381
END DESCRIPTION:
XS GIS Cut Line= 3
      1540297.91      6848846.83      1541047.92       6847961.4
      1541661.05      6847493.76
#Sta/Elev= 30
  3982.3 1819.39  4021.6 1820.21  4035.8 1818.89  4589.5 1813.26  4767.1 1811.97
  4909.3 1812.51  4998.2 1810.25  4998.7 1809.75  5004.8 1810.25  5008.1 1811.48
  5207.1 1814.88  5300.6 1814.54  5342.2 1815.63  5350.5 1814.34  5356.8 1816.36
    5365 1814.86  5371.3 1816.97  5385.8 1812.74  5392.1 1814.37  5400.4 1813.71
  5406.6  1815.8  5570.8 1820.15  5692.4 1820.74    5706 1822.85  5742.7 1824.26
  5749.6 1822.76  5755.9 1824.12  5834.8 1822.88  5870.2 1824.04  5913.8 1822.77
#Mann= 3 ,-1 , 0
  3982.3     .07       0  4998.2     .07       0  5004.8     .07       0
Bank Sta=4998.2,5004.8
XS Rating Curve= 0 ,0
Exp/Cntr=0.3,0.1

Type RM Length L Ch R = 1 ,42995   ,432,432,432
BEGIN DESCRIPTION:
Indian Creek 42995
END DESCRIPTION:
XS GIS Cut Line= 3
      1540381.26      6848961.39      1541131.25      6848570.77
      1541989.53       6847712.5
#Sta/Elev= 30
  4150.4 1818.83  4214.2 1818.15  4280.5 1818.76  4319.1 1817.79  4324.7 1818.87
  4341.2 1819.04  4413.9 1816.73  4490.3 1815.71  4926.6 1810.86  4948.7 1811.46
  4965.2 1810.48  4974.3 1807.43  4974.8 1806.93  4981.1 1807.43  4992.9 1809.16
  5078.4 1809.17  5127.9 1808.23  5212.8 1810.65    5234 1809.65  5297.6 1809.19
  5424.9 1811.63  5460.2 1813.54  5488.5 1814.35  5495.6  1813.8  5502.7 1815.02
  5516.8 1815.38  5559.2  1816.1  5622.9 1815.75  5912.8 1819.92  6209.8  1820.5
#Mann= 3 ,-1 , 0
  4150.4     .07       0  4974.3     .07       0  4981.1     .07       0
Bank Sta=4974.3,4981.1
XS Rating Curve= 0 ,0
Exp/Cntr=0.3,0.1

Type RM Length L Ch R = 1 ,42563   ,180,180,180
BEGIN DESCRIPTION:
Indian Creek 42562.69
END DESCRIPTION:
XS GIS Cut Line= 3
      1540553.11      6849086.41      1541521.88      6848602.02
      1542224.55      6847852.51
#Sta/Elev= 30
  3919.4 1818.21  3999.8 1817.11  4083.6 1817.34  4122.7 1816.24  4240.1 1816.47
  4262.5 1815.32  4379.9  1813.7  4569.9 1811.29    4693 1810.81  4804.8 1808.78
  4871.8 1809.39  4955.6 1807.89  4972.4  1807.1    4980 1805.74  4980.5 1805.24
  4987.3 1805.74  5035.7 1806.81    5064 1808.05  5071.3 1809.19  5134.8 1808.83
  5241.1  1810.6  5382.4 1815.96  5446.4 1815.48  5613.3 1817.82  5729.2 1819.58
  5792.3 1819.26  5835.6 1819.62  5911.6 1819.79  5999.4 1819.68  6029.9 1819.82
#Mann= 8 ,-1 , 0
  3919.4     .07       0    4980     .07       0  4987.3     .07       0
  5613.3    .035       0  5792.3     .07       0  5835.6    .035       0
  5911.6     .07       0  5999.4    .035       0
Bank Sta=4980,4987.3
XS Rating Curve= 0 ,0
Exp/Cntr=0.3,0.1

Type RM Length L Ch R = 1 ,42383   ,368,368,368
BEGIN DESCRIPTION:
Indian Creek 42383.28
END DESCRIPTION:
XS GIS Cut Line= 3
      1540803.13      6849195.77      1541672.92      6848669.73
      1542360.23      6847883.49
#Sta/Elev= 30
  3974.6 1816.24    4024 1816.42  4097.7 1815.11  4156.7 1815.46  4246.6 1813.56
  4303.3 1813.91  4309.2 1813.06  4330.5  1814.2    4346 1813.83  4351.9 1812.68
  4419.7 1811.75  4788.4 1808.08  4843.5 1808.02  4935.1 1807.59  4958.5 1806.29
  5015.2 1806.06  5025.7    1805  5026.2  1804.5  5033.1    1805  5043.7  1807.5
  5057.9 1808.93  5142.4 1809.11  5185.1 1810.08  5213.6 1812.22    5242 1812.33
  5262.9 1813.46  5284.7 1815.51  5580.4 1817.61  5687.1 1818.89  6035.4 1819.72
#Mann= 9 ,-1 , 0
  3974.6     .07       0  4156.7    .045       0  4246.6     .07       0
  4788.4    .035       0  4843.5     .07       0  5025.7     .07       0
  5033.1     .07       0  5580.4    .035       0  5687.1     .07       0
Bank Sta=5025.7,5033.1
XS Rating Curve= 0 ,0
Exp/Cntr=0.3,0.1

Type RM Length L Ch R = 1 ,42015   ,405,405,405
BEGIN DESCRIPTION:
Indian Creek 41979
END DESCRIPTION:
XS GIS Cut Line= 3
       1541394.2      6849256.35      1541698.84      6848975.27
      1542324.61      6848382.43
#Sta/Elev= 30
  4625.6 1809.53  4768.2 1808.77  4816.3 1808.61  4823.1 1809.47  4844.4  1809.7
  4872.4    1808  4922.3 1808.07  4930.8 1807.48  4936.5 1806.72  4979.1 1807.26
  4996.3  1804.4  4996.8  1803.9  5003.3  1803.9  5003.8  1804.4  5014.2 1805.18
  5056.7 1805.16  5099.2  1806.2  5184.1 1806.16  5198.3 1806.31  5205.2  1807.3
  5240.8 1806.79  5346.7 1808.02  5488.3 1810.03  5665.5 1813.56  5778.4 1815.82
  5799.4 1816.84  5806.3 1817.85  5812.4 1817.65  5848.8 1817.06  5902.1 1817.58
#Mann= 7 ,-1 , 0
  4625.6    .045       0  4768.2     .07       0  4930.8    .035       0
  4996.3    .035       0  5003.8    .035       0  5665.5     .07       0
  5812.4    .035       0
Bank Sta=4996.3,5003.8
XS Rating Curve= 0 ,0
Exp/Cntr=0.3,0.1

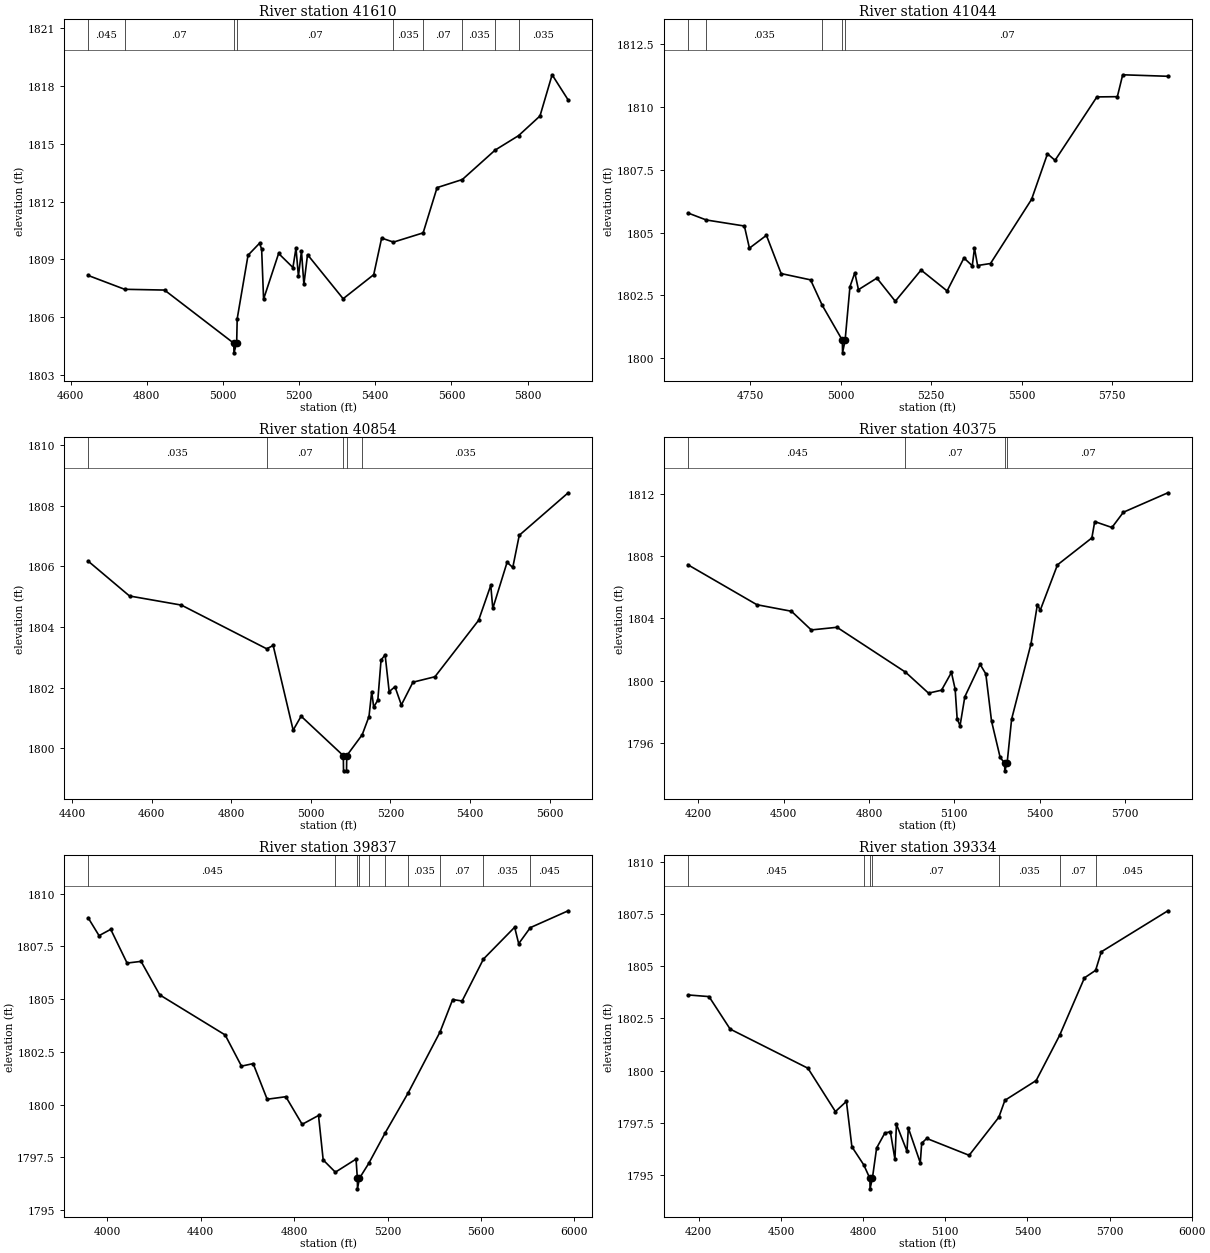
Type RM Length L Ch R = 1 ,41610   ,566,566,566
BEGIN DESCRIPTION:
Indian Creek 12.0
END DESCRIPTION:
XS GIS Cut Line= 5
      1541605.11      6849234.18      1541988.76      6849108.32
      1542094.38      6849117.74      1542144.31      6849077.42
      1542332.85      6848416.79
#Sta/Elev= 30
  4645.7 1808.17  4741.7 1807.45  4846.4 1807.41  5028.3 1804.65  5028.8 1804.15
  5035.9 1804.65  5037.3 1805.92  5065.8 1809.22  5095.9 1809.84  5101.5 1809.54
  5106.6 1806.94  5146.1 1809.31  5183.7 1808.58  5191.7 1809.59  5198.1 1808.14
  5206.1 1809.43  5212.5  1807.7    5222 1809.25  5315.6 1806.96  5395.9 1808.21
  5416.7 1810.11  5447.8  1809.9  5525.7 1810.38  5562.3 1812.73  5628.6 1813.15
  5714.9 1814.68  5776.4 1815.43  5832.6 1816.45  5864.5 1818.59  5906.7 1817.28
#Mann= 9 ,-1 , 0
  4645.7    .045       0  4741.7     .07       0  5028.3     .07       0
  5035.9     .07       0  5447.8    .035       0  5525.7     .07       0
  5628.6    .035       0  5714.9     .07       0  5776.4    .035       0
Bank Sta=5028.3,5035.9
XS Rating Curve= 0 ,0
Exp/Cntr=0.3,0.1

Type RM Length L Ch R = 1 ,41044   ,190,190,190
BEGIN DESCRIPTION:
Indian Creek 41216.83
END DESCRIPTION:
XS GIS Cut Line= 4
      1541991.26      6849303.85      1542272.41      6849251.68
      1542746.89      6849343.79      1543202.78      6849021.32
#Sta/Elev= 30
  4576.7 1805.78  4627.7  1805.5  4733.1 1805.26  4747.1 1804.38  4794.1 1804.89
  4834.8 1803.37  4916.2 1803.12  4948.4 1802.11  5004.1 1800.72  5004.6 1800.22
  5011.7 1800.72  5025.1 1802.85  5038.5  1803.4  5048.6 1802.73  5099.6 1803.19
  5150.5 1802.27  5221.8 1803.51  5293.8 1802.68  5340.4 1803.99  5363.4 1803.68
  5369.5 1804.38  5378.1 1803.69  5413.8 1803.77  5527.4 1806.32  5571.4 1808.13
  5592.3 1807.87    5708 1810.39  5764.6  1810.4  5779.4 1811.27  5904.4 1811.21
#Mann= 5 ,-1 , 0
  4576.7     .07       0  4627.7    .035       0  4948.4     .07       0
  5004.1     .07       0  5011.7     .07       0
Bank Sta=5004.1,5011.7
XS Rating Curve= 0 ,0
Exp/Cntr=0.3,0.1

Type RM Length L Ch R = 1 ,40854   ,479,479,479
BEGIN DESCRIPTION:
Indian Creek 40844.5
END DESCRIPTION:
XS GIS Cut Line= 3
       1541951.3      6849390.96      1542674.26      6849443.78
      1543145.35      6849541.48
#Sta/Elev= 30
  4440.5 1806.17  4544.5 1805.02  4674.8 1804.72  4889.2 1803.28  4905.4 1803.39
  4955.6  1800.6  4975.6 1801.06  5081.6 1799.76  5082.1 1799.26  5089.7 1799.26
  5090.2 1799.76  5129.1 1800.45  5146.1 1801.05  5152.9 1801.87  5157.9 1801.36
  5168.3 1801.59  5176.4 1802.91  5186.6 1803.08  5196.8 1801.87  5211.4 1802.03
  5227.4 1801.43  5256.5 1802.18  5311.8 1802.36  5421.5 1804.22    5452 1805.37
  5457.1 1804.61    5493 1806.13  5507.3 1805.96  5523.6 1807.02  5646.5 1808.42
#Mann= 5 ,-1 , 0
  4440.5    .035       0  4889.2     .07       0  5081.6     .07       0
  5090.2     .07       0  5129.1    .035       0
Bank Sta=5081.6,5090.2
XS Rating Curve= 0 ,0
Exp/Cntr=0.3,0.1

Type RM Length L Ch R = 1 ,40375   ,538,538,538
BEGIN DESCRIPTION:
Indian Creek 39957.473
END DESCRIPTION:
XS GIS Cut Line= 3
      1541823.55      6849953.63      1542755.91      6849847.87
      1543500.27      6849751.54
#Sta/Elev= 30
  4162.7 1807.45  4405.7 1804.88  4527.3 1804.46  4596.9 1803.26  4687.5 1803.43
  4928.4 1800.55  5009.5  1799.2  5055.2 1799.39  5090.1 1800.53  5103.1 1799.46
  5110.2 1797.56  5120.3  1797.1  5137.2 1798.97  5190.9 1801.05    5211 1800.44
  5231.2  1797.4  5261.5 1795.07  5277.3 1794.71  5277.8 1794.21    5286 1794.71
  5301.8 1797.53    5370 1802.37  5392.5 1804.89  5402.6 1804.53  5463.1 1807.44
  5584.1 1809.17  5594.2 1810.22  5654.7 1809.84    5695 1810.82  5851.6 1812.07
#Mann= 4 ,-1 , 0
  4162.7    .045       0  4928.4     .07       0  5277.3     .07       0
    5286     .07       0
Bank Sta=5277.3,5286
XS Rating Curve= 0 ,0
Exp/Cntr=0.3,0.1

Type RM Length L Ch R = 1 ,39837   ,503,503,503
BEGIN DESCRIPTION:
Indian Creek 39837
END DESCRIPTION:
XS GIS Cut Line= 3
      1541678.15      6850315.57      1542756.25       6850336.4
      1543725.03      6850200.98
#Sta/Elev= 30
  3917.5 1808.86  3964.4 1808.01  4014.4 1808.31  4084.4 1806.71  4144.4 1806.79
  4224.4  1805.2  4504.5  1803.3  4574.5 1801.82  4624.5 1801.94  4684.5 1800.25
  4764.5 1800.37  4834.5 1799.06  4904.5 1799.48  4924.5 1797.37  4976.7 1796.79
  5065.2 1797.41  5070.9  1796.5  5071.4    1796  5079.7  1796.5  5119.8 1797.21
  5190.9 1798.67  5288.5 1800.55    5425 1803.44  5479.2 1804.98  5519.6 1804.91
    5611  1806.9  5744.7 1808.41  5761.9 1807.63  5811.7 1808.39    5974 1809.19
#Mann= 10 ,-1 , 0
  3917.5    .045       0  4976.7     .07       0  5070.9     .07       0
  5079.7     .07       0  5119.8    .035       0  5190.9     .07       0
  5288.5    .035       0    5425     .07       0    5611    .035       0
  5811.7    .045       0
Bank Sta=5070.9,5079.7
XS Rating Curve= 0 ,0
Exp/Cntr=0.3,0.1

Type RM Length L Ch R = 1 ,39334   ,417,417,417
BEGIN DESCRIPTION:
Indian Creek 39570.07
END DESCRIPTION:
XS GIS Cut Line= 4
      1542117.84      6850670.04      1542873.24      6850732.83
      1542991.03      6850758.98      1543799.94      6850426.34
#Sta/Elev= 30
  4159.9 1803.63  4237.3 1803.55  4314.5 1801.99  4598.6 1800.11  4698.9 1798.03
  4739.1 1798.52  4759.1 1796.34  4802.5 1795.47  4824.9 1794.82  4825.4 1794.32
  4833.9 1794.82  4849.4 1796.28  4879.5    1797  4899.6 1797.06  4916.3 1795.74
  4921.8 1797.42  4960.2 1796.13  4965.3 1797.24  5008.9 1795.57    5014 1796.51
  5032.4 1796.74  5187.3 1795.93  5295.9 1797.76  5317.9 1798.57  5432.1 1799.52
  5517.8 1801.69  5608.5 1804.45  5649.2 1804.81    5670  1805.7  5913.2 1807.67
#Mann= 7 ,-1 , 0
  4159.9    .045       0  4802.5     .07       0  4824.9     .07       0
  4833.9     .07       0  5295.9    .035       0  5517.8     .07       0
  5649.2    .045       0
Bank Sta=4824.9,4833.9
XS Rating Curve= 0 ,0
Exp/Cntr=0.3,0.1

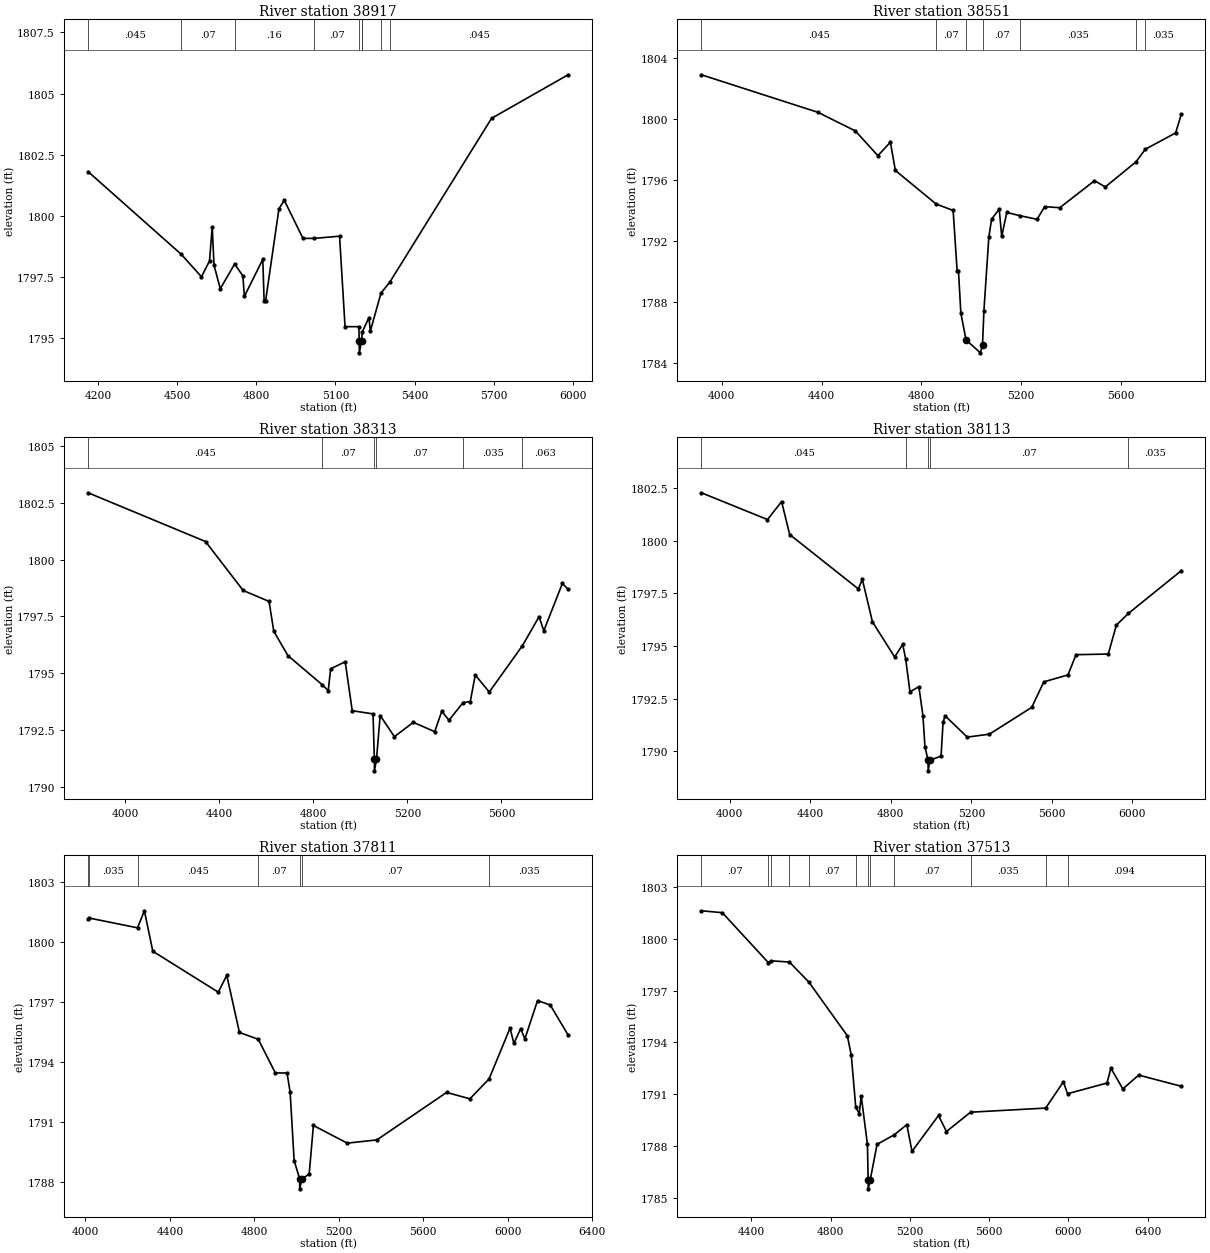
Type RM Length L Ch R = 1 ,38917   ,366,366,366
BEGIN DESCRIPTION:
Indian Creek 39234.33
END DESCRIPTION:
XS GIS Cut Line= 6
      1542402.39      6851099.16       1542979.2      6850993.59
      1543197.04      6851019.46      1543252.59      6851001.42
       1543260.3       6850918.2      1544091.86      6850658.52
#Sta/Elev= 30
  4162.7 1801.81  4515.5 1798.43  4592.3 1797.51  4622.8 1798.16    4633 1799.55
  4639.7 1797.99  4663.5 1797.02  4717.8 1798.03  4749.1 1797.55  4754.9 1796.71
  4824.6 1798.22  4829.7 1796.51  4835.5 1796.54  4885.8 1800.29    4906 1800.64
  4976.8 1799.08  5019.2 1799.08  5115.5 1799.17  5136.3 1795.47  5188.7 1795.47
    5190  1794.9  5190.5  1794.4    5199  1794.9  5201.8 1795.26  5226.9 1795.84
  5232.2 1795.29  5272.4 1796.84  5306.4  1797.3  5691.6 1803.99  5981.6 1805.77
#Mann= 9 ,-1 , 0
  4162.7    .045       0  4515.5     .07       0  4717.8     .16       0
  5019.2     .07       0    5190     .07       0    5199     .07       0
  5201.8    .035       0  5272.4     .07       0  5306.4    .045       0
Bank Sta=5190,5199
XS Rating Curve= 0 ,0
Exp/Cntr=0.3,0.1

Type RM Length L Ch R = 1 ,38551   ,238,238,238
BEGIN DESCRIPTION:
Indian Creek 38551.37
END DESCRIPTION:
XS GIS Cut Line= 5
      1542178.48      6851295.08      1543138.52      6851337.69
      1543261.46      6851367.65      1543340.27      6851385.71
      1544086.59      6851270.03
#Sta/Elev= 30
  3918.6  1802.9  4385.6 1800.44  4535.7 1799.22  4625.8  1797.6  4675.9 1798.48
  4695.9 1796.63  4859.3 1794.43  4927.4 1794.01  4943.6 1790.01  4948.7 1790.06
  4958.3 1787.29  4978.9 1785.53  5036.5 1784.68  5045.1 1785.18  5050.8 1787.45
  5070.5 1792.27  5081.6 1793.44    5112  1794.1  5122.1 1792.31  5142.4 1793.88
    5197 1793.66  5263.8 1793.43  5294.1 1794.26  5354.9 1794.19  5493.9 1795.96
    5537 1795.55  5659.8 1797.19  5697.6 1798.02    5819 1799.09  5842.2 1800.33
#Mann= 7 ,-1 , 0
  3918.6    .045       0  4859.3     .07       0  4978.9     .04       0
  5045.1     .07       0    5197    .035       0  5659.8    .063       0
  5697.6    .035       0
Bank Sta=4978.9,5045.1
XS Rating Curve= 0 ,0
Exp/Cntr=0.3,0.1

Type RM Length L Ch R = 1 ,38313   ,200,200,200
BEGIN DESCRIPTION:
Indian Creek 10.0
END DESCRIPTION:
XS GIS Cut Line= 5
      1542156.27      6851515.91       1543136.7      6851567.39
      1543275.17      6851603.66      1543342.28      6851571.62
      1544177.59      6851460.24
#Sta/Elev= 30
  3841.8 1802.93  4341.2 1800.79  4501.4 1798.64  4611.6 1798.16  4631.6 1796.85
  4691.7 1795.78  4837.8  1794.5  4863.2 1794.24  4873.5  1795.2  4935.5 1795.51
  4965.4 1793.36  5053.9 1793.22  5059.5 1791.22    5060 1790.72  5068.6 1791.22
  5084.2 1793.15  5144.7 1792.22  5225.4 1792.85  5316.2 1792.44  5346.5 1793.34
  5376.8 1792.94  5437.1 1793.72  5467.6 1793.76  5488.7 1794.93  5548.3 1794.18
  5689.7 1796.22  5760.1 1797.49  5780.3 1796.87  5859.4 1798.95  5883.8 1798.69
#Mann= 6 ,-1 , 0
  3841.8    .045       0  4837.8     .07       0  5059.5     .07       0
  5068.6     .07       0  5437.1    .035       0  5689.7    .063       0
Bank Sta=5059.5,5068.6
XS Rating Curve= 0 ,0
Exp/Cntr=0.3,0.1

Type RM Length L Ch R = 1 ,38113   ,302,302,302
BEGIN DESCRIPTION:
Indian Creek 38112.6
END DESCRIPTION:
XS GIS Cut Line= 3
      1542167.71      6851716.61      1543303.13      6851789.52
      1544547.96      6851784.31
#Sta/Elev= 30
  3860.2 1802.27  4188.2    1801  4258.3 1801.85  4298.4 1800.29  4639.1 1797.71
  4659.1 1798.16  4709.2 1796.15  4819.5 1794.48  4859.5 1795.08  4873.9  1794.4
  4895.4 1792.83  4939.7 1793.07  4959.8  1791.7  4969.8 1790.23  4985.2 1789.58
  4985.7 1789.08  4994.5 1789.58  5049.8 1789.78  5059.8 1791.39  5069.8 1791.69
  5179.8 1790.68  5289.8 1790.82  5499.8 1792.09  5559.8  1793.3  5679.8 1793.63
  5719.8 1794.59  5879.8 1794.62  5919.8 1795.99    5980 1796.55  6242.8 1798.58
#Mann= 5 ,-1 , 0
  3860.2    .045       0  4873.9     .07       0  4985.2     .07       0
  4994.5     .07       0    5980    .035       0
Bank Sta=4985.2,4994.5
XS Rating Curve= 0 ,0
Exp/Cntr=0.3,0.1

Type RM Length L Ch R = 1 ,37811   ,298,298,298
BEGIN DESCRIPTION:
Indian Creek 37810.92
END DESCRIPTION:
XS GIS Cut Line= 3
      1542318.72      6852128.07      1543297.92      6852091.61
      1544589.59      6852018.69
#Sta/Elev= 30
  4012.9 1801.13  4016.9 1801.19    4247  1800.7  4279.4 1801.55  4319.4 1799.53
  4629.6 1797.49  4669.6 1798.33  4729.7 1795.48  4818.9 1795.14  4899.8 1793.46
  4955.1 1793.46  4969.8  1792.5  4988.8 1789.09  5014.9 1788.18  5015.4 1787.68
    5025 1788.18    5060 1788.41    5080 1790.84  5240.3 1789.96  5380.5 1790.12
    5711 1792.49  5821.2 1792.17    5912 1793.16  6011.5  1795.7  6029.6 1794.93
  6061.6 1795.67  6081.6 1795.16  6141.7 1797.07  6201.8 1796.85  6286.5 1795.35
#Mann= 7 ,-1 , 0
  4012.9     .07       0  4016.9    .035       0    4247    .045       0
  4818.9     .07       0  5014.9     .07       0    5025     .07       0
    5912    .035       0
Bank Sta=5014.9,5025
XS Rating Curve= 0 ,0
Exp/Cntr=0.3,0.1

Type RM Length L Ch R = 1 ,37513   ,228,228,228
BEGIN DESCRIPTION:
Indian Creek 37512.54
END DESCRIPTION:
XS GIS Cut Line= 3
      1542459.41      6852430.15      1543292.71      6852388.48
      1544880.66      6852419.72
#Sta/Elev= 30
  4148.4 1801.63  4254.1 1801.52  4485.9 1798.63  4502.2 1798.73  4592.6 1798.66
    4690 1797.51  4884.9 1794.39  4904.9 1793.26  4927.4 1790.26    4945 1789.87
    4955  1790.9  4986.4 1788.09    4990 1786.02  4990.5 1785.52  5000.1 1786.02
    5035  1788.1  5121.8 1788.65  5185.1 1789.24  5211.3 1787.69  5345.1 1789.77
  5385.1 1788.84  5506.7 1789.96    5886  1790.2  5975.2 1791.72  5996.3 1791.03
  6195.3 1791.65  6215.3 1792.51  6275.3 1791.31  6355.3 1792.11    6571 1791.46
#Mann= 12 ,-1 , 0
  4148.4     .07       0  4485.9    .035       0  4502.2     .07       0
  4592.6    .035       0    4690     .07       0  4927.4    .035       0
    4990    .035       0  5000.1    .035       0  5121.8     .07       0
  5506.7    .035       0    5886    .063       0  5996.3    .094       0
Bank Sta=4990,5000.1
XS Rating Curve= 0 ,0
Exp/Cntr=0.3,0.1

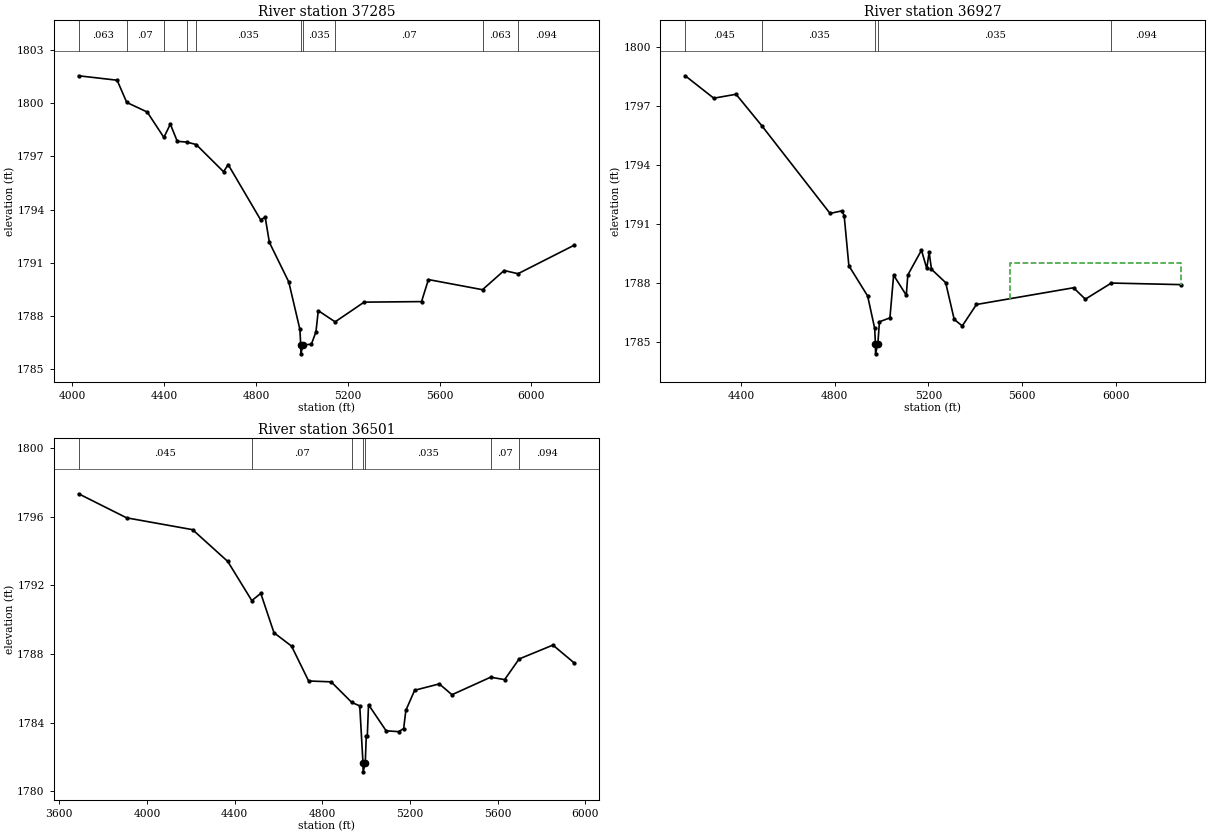
Type RM Length L Ch R = 1 ,37285   ,358,358,358
BEGIN DESCRIPTION:
Indian Creek 37284.71
END DESCRIPTION:
XS GIS Cut Line= 3
       1542438.6       6852456.2       1543407.3      6852581.19
      1544589.62      6852591.61
#Sta/Elev= 30
  4026.7 1801.53  4194.5 1801.28  4236.4 1800.03  4325.6 1799.49  4398.3 1798.06
  4426.4 1798.81  4456.6 1797.84  4497.7  1797.8  4539.1 1797.66  4658.3 1796.13
  4678.5 1796.53  4819.6 1793.43  4839.8 1793.57  4858.1 1792.15  4942.5 1789.93
    4991 1787.26  4994.7 1786.38  4995.2 1785.88  5004.9 1786.38  5041.1 1786.42
  5061.1 1787.12  5071.1 1788.31  5144.6 1787.68  5271.1 1788.79  5521.2 1788.82
  5551.2 1790.06  5786.9 1789.49  5881.2 1790.57  5941.8 1790.39  6185.8 1791.99
#Mann= 10 ,-1 , 0
  4026.7    .063       0  4236.4     .07       0  4398.3    .035       0
  4497.7     .07       0  4539.1    .035       0  4994.7    .035       0
  5004.9    .035       0  5144.6     .07       0  5786.9    .063       0
  5941.8    .094       0
Bank Sta=4994.7,5004.9
XS Rating Curve= 0 ,0
Exp/Cntr=0.3,0.1

Type RM Length L Ch R = 1 ,36927   ,426,426,426
BEGIN DESCRIPTION:
Indian Creek 36927.49
END DESCRIPTION:
XS GIS Cut Line= 3
      1542568.72      6853003.07      1543386.46      6852935.36
      1544667.68      6853122.85
#Sta/Elev= 30
  4161.4 1798.52  4283.2 1797.38  4378.4 1797.58  4488.3 1795.98  4779.8 1791.52
    4830 1791.65    4840 1791.41  4860.1 1788.86  4940.3 1787.32  4970.4 1785.67
  4973.5 1784.88    4974 1784.38  4983.8 1784.88  4990.6 1786.01  5035.4 1786.21
  5051.2 1788.38  5105.3 1787.36  5111.8 1788.39  5170.1 1789.65  5192.7 1788.72
  5202.8 1789.55  5212.9 1788.68  5273.5    1788  5309.9 1786.13  5344.3  1785.8
  5404.9 1786.89  5819.3 1787.74  5869.8 1787.16  5980.9 1787.98  6276.8  1787.9
#Mann= 5 ,-1 , 0
  4161.4    .045       0  4488.3    .035       0  4973.5    .035       0
  4983.8    .035       0  5980.9    .094       0
#XS Ineff= 2 , 0
       0                    5550       0    1789
Permanent Ineff=
       F       F
Bank Sta=4973.5,4983.8
XS Rating Curve= 0 ,0
Exp/Cntr=0.3,0.1

Type RM Length L Ch R = 1 ,36501   ,243,243,243
BEGIN DESCRIPTION:
Indian Creek 36500.83
END DESCRIPTION:
XS GIS Cut Line= 3
      1542396.91      6853310.35      1543709.38      6853200.98
      1544651.03      6853148.96
#Sta/Elev= 30
  3688.4 1797.33  3907.2 1795.93  4208.3 1795.24  4368.8 1793.39  4478.5 1791.11
  4519.4 1791.53  4579.6 1789.24  4659.8 1788.46  4737.7 1786.43  4840.5 1786.38
  4934.7 1785.18  4970.9 1784.98  4985.8 1781.64  4986.3 1781.14  4996.1 1781.64
  5000.7 1783.23  5005.4 1783.23    5011 1785.05  5091.2 1783.53  5148.2 1783.48
  5171.3 1783.66  5181.3 1784.72  5221.4 1785.89    5334 1786.26  5391.6 1785.63
    5568 1786.65    5632 1786.51  5697.8 1787.71  5852.3 1788.52  5948.5 1787.49
#Mann= 7 ,-1 , 0
  3688.4    .045       0  4478.5     .07       0  4934.7    .035       0
  4985.8    .035       0  4996.1    .035       0    5568     .07       0
  5697.8    .094       0
Bank Sta=4985.8,4996.1
XS Rating Curve= 0 ,0
Exp/Cntr=0.3,0.1