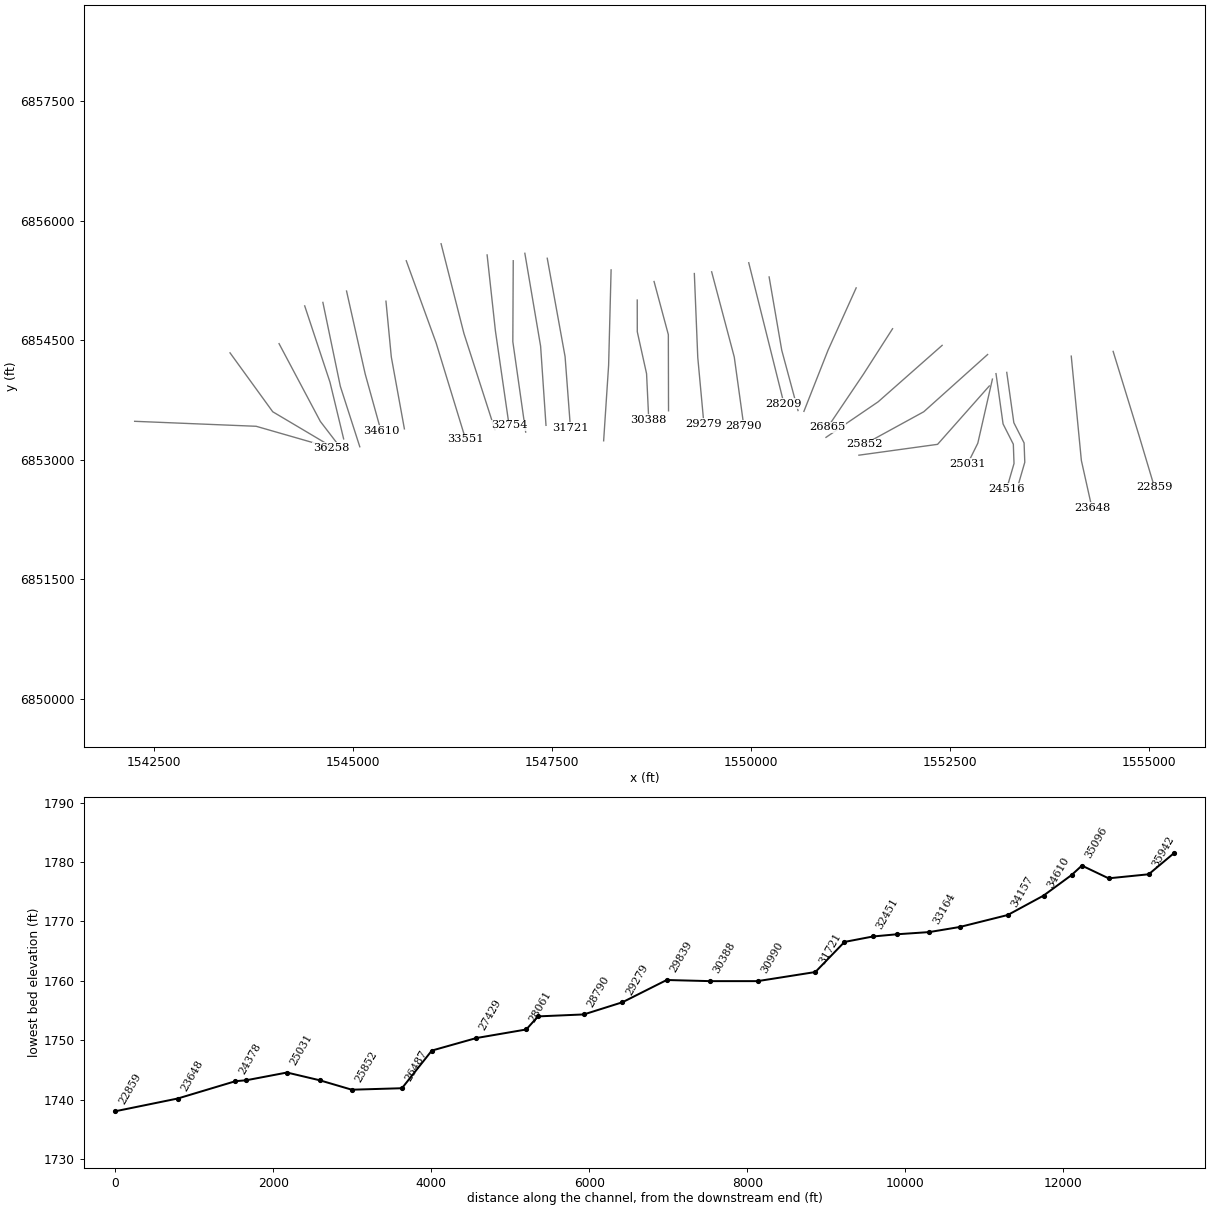
HEC-RAS study Indian Creek.prj: Indian Creek Base Level Engineering

--- Indian Creek.g01 (geometry) --- (continued)

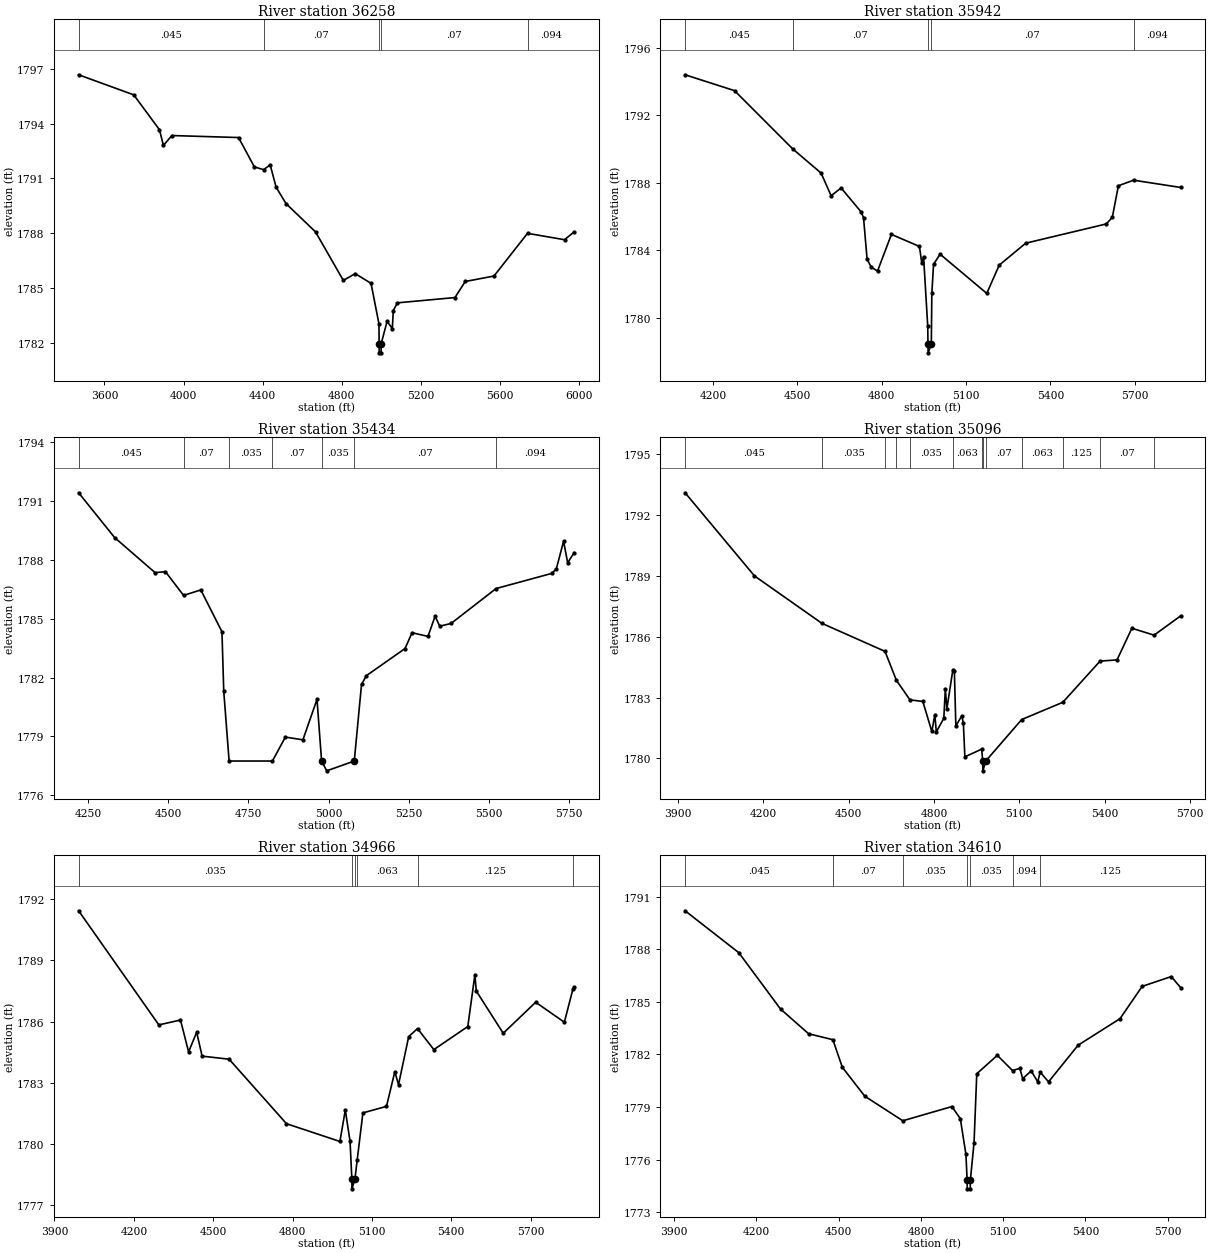
Type RM Length L Ch R = 1 ,36258   ,316,316,316
BEGIN DESCRIPTION:
Indian Creek 36257.87
END DESCRIPTION:
XS GIS Cut Line= 3
      1542256.29      6853482.23       1543782.3      6853419.73
      1544724.98      6853148.91
#Sta/Elev= 30
  3469.2 1796.68  3748.1 1795.58  3878.2 1793.67  3898.3 1792.81  3941.2 1793.35
  4278.6 1793.24  4358.7 1791.63  4405.1 1791.48  4438.7 1791.74  4468.7 1790.52
  4518.8 1789.62  4668.1 1788.07    4809 1785.41  4869.1 1785.78  4949.1 1785.25
  4989.2 1783.03  4990.1 1781.94  4990.6 1781.44    5000 1781.44  5000.5 1781.94
  5030.5 1783.17  5056.8 1782.77    5062 1783.76  5082.5 1784.18  5373.9 1784.47
  5425.9 1785.35  5571.5 1785.65  5741.1 1787.99  5928.4 1787.64  5977.3 1788.07
#Mann= 5 ,-1 , 0
  3469.2    .045       0  4405.1     .07       0  4990.1     .07       0
  5000.5     .07       0  5741.1    .094       0
Bank Sta=4990.1,5000.5
XS Rating Curve= 0 ,0
Exp/Cntr=0.3,0.1

Type RM Length L Ch R = 1 ,35942   ,508,508,508
BEGIN DESCRIPTION:
Indian Creek 35941.53
END DESCRIPTION:
XS GIS Cut Line= 3
      1543454.17      6854341.61      1543990.63      6853602.02
      1544719.76      6853169.76
#Sta/Elev= 30
  4101.3 1794.39    4277 1793.45  4483.3 1790.01  4584.7 1788.57  4620.3 1787.23
  4655.9 1787.69    4727 1786.27  4735.5 1785.93  4748.2 1783.47  4762.6 1783.01
  4785.2 1782.77  4834.6 1784.94  4934.2 1784.23  4942.7 1783.22  4948.9 1783.63
  4963.6 1779.53  4964.7 1778.43  4965.2 1777.93  4976.4 1778.43  4978.3 1781.45
  4984.4 1783.17  5007.6 1783.77  5173.5 1781.45  5217.7 1783.12  5311.8 1784.42
  5598.4 1785.56  5619.8 1785.95  5641.3 1787.82  5695.1 1788.15  5862.6 1787.72
#Mann= 5 ,-1 , 0
  4101.3    .045       0  4483.3     .07       0  4964.7     .07       0
  4976.4     .07       0  5695.1    .094       0
Bank Sta=4964.7,4976.4
XS Rating Curve= 0 ,0
Exp/Cntr=0.3,0.1

Type RM Length L Ch R = 1 ,35434   ,338,338,338
BEGIN DESCRIPTION:
Indian Creek 9.0
END DESCRIPTION:
XS GIS Cut Line= 3
      1544070.06      6854457.04      1544588.65      6853480.65
      1544856.31      6853131.89
#Sta/Elev= 30
  4220.8 1791.42  4332.9 1789.14  4459.2 1787.35  4491.5  1787.4  4548.1 1786.19
  4601.7 1786.47  4667.7 1784.34  4673.3 1781.31    4690 1777.75    4825 1777.75
  4865.5 1778.97  4920.1 1778.83  4964.1 1780.89  4978.4 1777.75  4994.3 1777.25
  5080.3 1777.75  5102.9 1781.65    5118  1782.1  5238.5 1783.48  5260.5 1784.29
  5310.2  1784.1  5332.3 1785.13  5346.8 1784.62  5382.1 1784.76  5522.5 1786.54
  5695.8 1787.31  5710.3 1787.54    5733 1788.95  5745.7 1787.85    5766 1788.37
#Mann= 7 ,-1 , 0
  4220.8    .045       0  4548.1     .07       0    4690    .035       0
    4825     .07       0  4978.4    .035       0  5080.3     .07       0
  5522.5    .094       0
Bank Sta=4978.4,5080.3
XS Rating Curve= 0 ,0
Exp/Cntr=0.3,0.1

Type RM Length L Ch R = 1 ,35096   ,130,130,130
BEGIN DESCRIPTION:
Indian Creek 35158.46
END DESCRIPTION:
XS GIS Cut Line= 3
      1544392.14      6854931.13      1544709.85      6853972.79
      1544881.28      6853261.07
#Sta/Elev= 30
  3925.6  1793.1  4169.5    1789  4406.8 1786.66  4628.3 1785.28    4668 1783.86
    4716 1782.89  4761.2 1782.81  4792.8 1781.33  4803.3 1782.16  4808.6 1781.31
  4834.9 1781.98  4840.3 1783.44  4845.6 1782.44  4866.6 1784.36    4872 1784.31
  4877.2 1781.61  4898.1  1782.1  4903.7 1781.73  4908.9 1780.08  4968.1 1780.46
  4971.5 1779.89    4972 1779.39  4983.3 1779.89  5108.7 1781.92  5253.2 1782.77
  5384.1  1784.8  5443.7 1784.86  5495.9 1786.42    5574 1786.08  5667.3 1787.03
#Mann= 13 ,-1 , 0
  3925.6    .045       0  4406.8    .035       0  4628.3    .045       0
    4668     .07       0    4716    .035       0  4866.6    .063       0
  4968.1     .07       0  4971.5     .07       0  4983.3     .07       0
  5108.7    .063       0  5253.2    .125       0  5384.1     .07       0
    5574    .094       0
Bank Sta=4971.5,4983.3
XS Rating Curve= 0 ,0
Exp/Cntr=0.3,0.1

Type RM Length L Ch R = 1 ,34966   ,356,356,356
BEGIN DESCRIPTION:
Indian Creek 34865.69
END DESCRIPTION:
XS GIS Cut Line= 3
      1544620.59       6854974.9      1544839.35      6853922.78
      1545084.02      6853162.71
#Sta/Elev= 30
  3991.4 1791.43  4294.6 1785.84  4376.4 1786.08    4407 1784.52  4437.6 1785.48
  4458.1 1784.31  4560.2 1784.16  4777.1    1781    4979 1780.13  4999.4 1781.67
  5017.4 1780.13  5024.1 1778.31  5024.6 1777.81    5036 1778.31  5044.3 1779.22
  5065.9 1781.53  5155.1 1781.85  5186.6 1783.55  5200.5 1782.91  5239.1 1785.27
  5272.4 1785.66  5334.1 1784.63  5462.4 1785.76  5489.2 1788.29  5494.5  1787.5
  5596.3 1785.43    5719 1786.95  5827.4 1785.97  5859.5 1787.58  5864.5 1787.69
#Mann= 6 ,-1 , 0
  3991.4    .035       0  5024.1    .035       0    5036    .035       0
  5044.3    .063       0  5272.4    .125       0  5859.5    .063       0
Bank Sta=5024.1,5036
XS Rating Curve= 0 ,0
Exp/Cntr=0.3,0.1

Type RM Length L Ch R = 1 ,34610   ,453,453,453
BEGIN DESCRIPTION:
Indian Creek 34609.66
END DESCRIPTION:
XS GIS Cut Line= 3
      1544917.72      6855117.62      1545152.09      6854075.98
      1545349.94      6853362.69
#Sta/Elev= 30
  3939.7 1790.19  4135.7  1787.8  4287.8 1784.59  4390.3 1783.18  4478.9 1782.84
  4513.3 1781.27  4595.3 1779.62    4734 1778.22  4913.1 1779.03  4943.8 1778.34
  4964.3  1776.3  4968.6 1774.84  4969.1 1774.34    4980 1774.34  4980.5 1774.84
  4993.9 1776.98  5003.8  1780.9  5078.8 1781.95  5134.4 1781.08  5160.9 1781.21
  5171.3 1780.62  5202.5 1781.06  5226.2 1780.44  5235.2 1780.99  5265.7 1780.44
  5373.7 1782.53  5526.4 1784.04  5607.2 1785.88  5713.3 1786.44  5747.6 1785.81
#Mann= 7 ,-1 , 0
  3939.7    .045       0  4478.9     .07       0    4734    .035       0
  4968.6    .035       0  4980.5    .035       0  5134.4    .094       0
  5235.2    .125       0
Bank Sta=4968.6,4980.5
XS Rating Curve= 0 ,0
Exp/Cntr=0.3,0.1

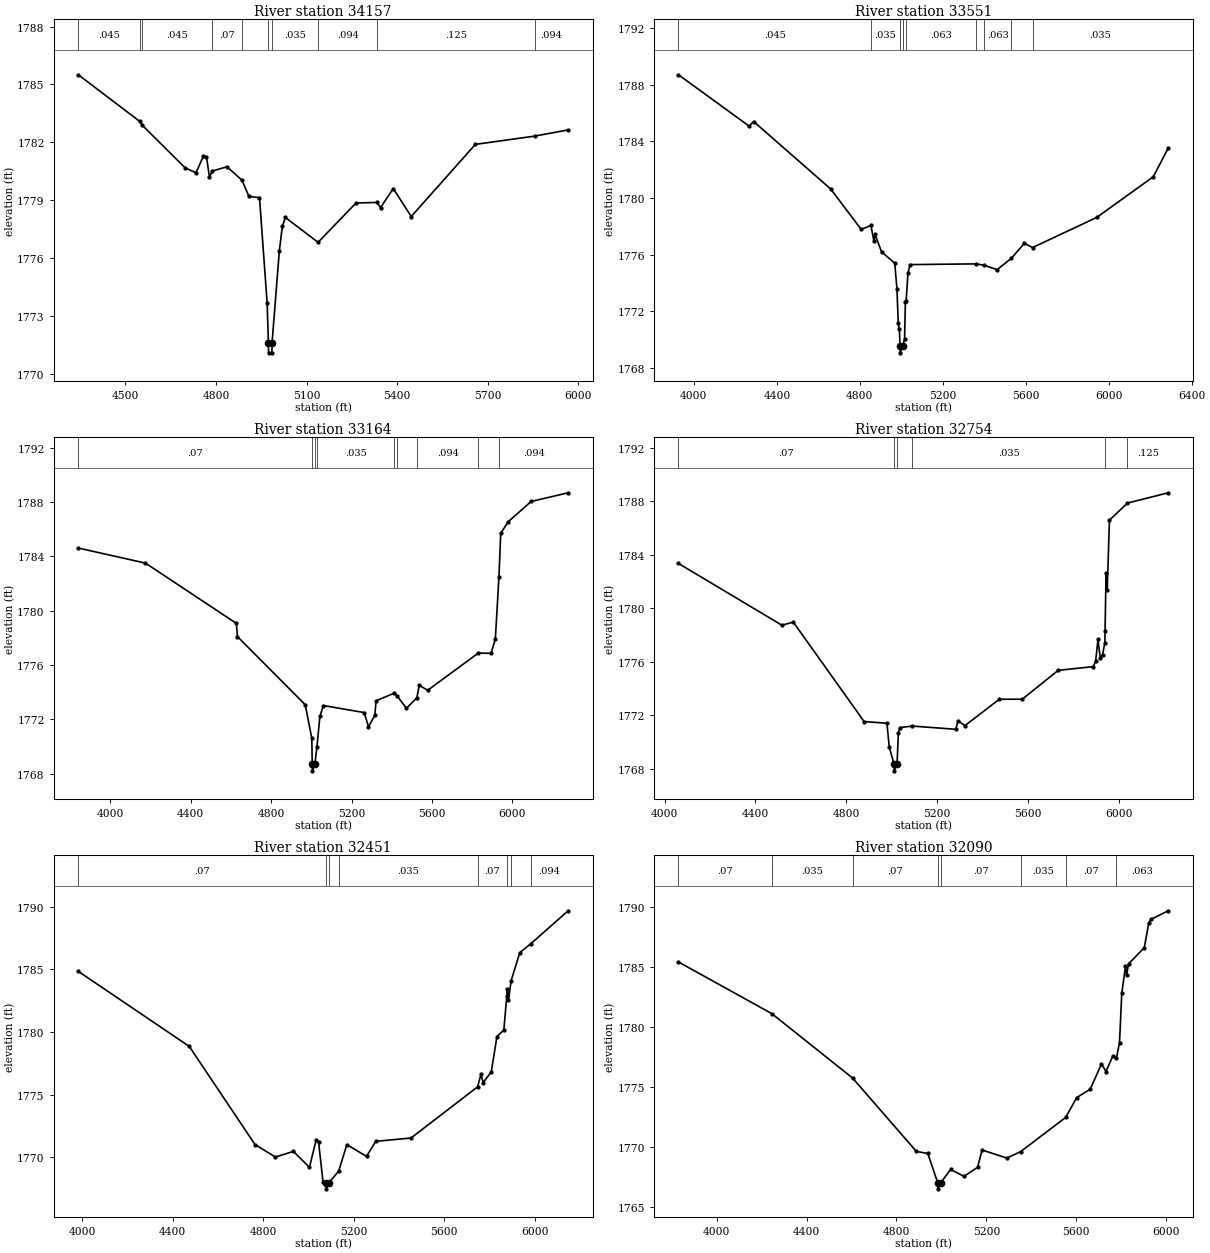
Type RM Length L Ch R = 1 ,34157   ,606,606,606
BEGIN DESCRIPTION:
Indian Creek 33996.18
END DESCRIPTION:
XS GIS Cut Line= 3
      1545412.79      6854990.06      1545479.97      6854289.71
      1545644.33      6853387.22
#Sta/Elev= 30
  4344.8  1785.5  4547.4 1783.09  4554.7 1782.91  4698.5 1780.67  4734.1 1780.42
  4758.8 1781.28  4768.8 1781.25  4778.8 1780.19  4788.5 1780.51  4836.7 1780.73
  4886.6 1780.03  4909.4 1779.19  4944.3 1779.13  4969.7 1773.64  4973.8 1771.58
  4974.3 1771.08  4985.3 1771.08  4985.8 1771.58  5009.9 1776.35  5019.9 1777.64
    5030  1778.1  5138.1 1776.81  5263.6 1778.85  5333.2 1778.88  5344.9 1778.61
    5387  1779.6  5446.5 1778.15  5658.7 1781.89  5854.9 1782.32  5965.7 1782.64
#Mann= 10 ,-1 , 0
  4344.8    .045       0  4547.4     .07       0  4554.7    .045       0
  4788.5     .07       0  4886.6    .035       0  4973.8    .035       0
  4985.8    .035       0  5138.1    .094       0  5333.2    .125       0
  5854.9    .094       0
Bank Sta=4973.8,4985.8
XS Rating Curve= 0 ,0
Exp/Cntr=0.3,0.1

Type RM Length L Ch R = 1 ,33551   ,387,387,387
BEGIN DESCRIPTION:
Indian Creek 33551.28
END DESCRIPTION:
XS GIS Cut Line= 3
      1545667.72      6855497.85      1546042.71      6854466.61
      1546412.52      6853258.23
#Sta/Elev= 30
  3925.9  1788.7  4266.2 1785.08  4288.3  1785.4  4659.4 1780.64    4807 1777.78
  4853.5 1778.07  4868.2 1776.94  4873.5 1777.43  4904.7  1776.2  4968.5  1775.4
  4979.2 1773.55  4985.2 1771.17  4990.6 1770.73    4994 1769.57  4994.5 1769.07
  5006.8 1769.57  5015.8 1770.03  5019.8 1772.69  5023.3 1772.71  5032.2 1774.72
  5042.7  1775.3  5361.6 1775.35  5399.9 1775.25  5462.2 1774.94    5531 1775.75
  5593.3  1776.8  5632.6  1776.5    5942 1778.63  6214.6  1781.5  6286.9 1783.53
#Mann= 9 ,-1 , 0
  3925.9    .045       0  4853.5    .035       0    4994    .035       0
  5006.8    .035       0  5023.3    .063       0  5361.6    .035       0
  5399.9    .063       0    5531    .125       0  5632.6    .035       0
Bank Sta=4994,5006.8
XS Rating Curve= 0 ,0
Exp/Cntr=0.3,0.1

Type RM Length L Ch R = 1 ,33164   ,410,410,410
BEGIN DESCRIPTION:
Indian Creek 33163.89
END DESCRIPTION:
XS GIS Cut Line= 3
      1546105.22      6855711.38      1546391.67       6854586.4
      1546782.28      6853372.89
#Sta/Elev= 30
  3841.2 1784.62  4174.9 1783.51  4627.2 1779.07  4632.3  1778.1  4969.5 1773.08
  5002.1 1770.62  5004.4 1768.71  5004.9 1768.21  5017.3 1768.71  5027.7 1769.96
  5042.4 1772.22    5060 1773.02    5263  1772.5    5284 1771.45  5315.6  1772.3
  5321.9 1773.37  5412.2 1773.93  5426.7 1773.72  5473.1 1772.82  5524.9 1773.59
  5536.2 1774.52  5578.2 1774.14  5830.8 1776.89  5893.3 1776.86    5915 1777.93
  5932.8 1782.48  5941.8 1785.71  5979.2 1786.56  6092.9 1788.05  6276.9 1788.69
#Mann= 9 ,-1 , 0
  3841.2     .07       0  5004.4     .07       0  5017.3     .07       0
  5027.7    .035       0  5412.2    .094       0  5426.7    .063       0
  5524.9    .094       0  5830.8    .063       0  5932.8    .094       0
Bank Sta=5004.4,5017.3
XS Rating Curve= 0 ,0
Exp/Cntr=0.3,0.1

Type RM Length L Ch R = 1 ,32754   ,303,303,303
BEGIN DESCRIPTION:
Indian Creek 32754.1
END DESCRIPTION:
XS GIS Cut Line= 3
      1546683.34      6855570.73       1546787.5      6854617.65
      1546959.17      6853431.57
#Sta/Elev= 30
  4060.8 1783.36  4516.2 1778.74  4566.5 1778.97  4878.4 1771.53    4979  1771.4
    4989 1769.63  5010.3 1768.34  5010.8 1767.84  5023.4 1768.34  5029.3 1770.64
  5035.7 1771.08  5091.2 1771.19  5281.9 1770.95    5292  1771.6  5322.3 1771.22
  5473.9  1773.2  5574.9  1773.2  5733.3 1775.36  5888.2 1775.64  5898.3 1776.08
  5908.4 1777.67  5918.5 1776.29  5928.6 1776.53  5938.7 1777.42  5939.6 1778.29
  5944.1 1782.66  5949.2 1781.38  5958.9  1786.6  6038.4 1787.88    6218 1788.65
#Mann= 6 ,-1 , 0
  4060.8     .07       0  5010.3     .07       0  5023.4     .07       0
  5091.2    .035       0  5939.6    .094       0  6038.4    .125       0
Bank Sta=5010.3,5023.4
XS Rating Curve= 0 ,0
Exp/Cntr=0.3,0.1

Type RM Length L Ch R = 1 ,32451   ,361,361,361
BEGIN DESCRIPTION:
Indian Creek 32450.82
END DESCRIPTION:
XS GIS Cut Line= 3
      1547011.46       6855497.9      1547006.25      6854482.23
      1547167.71      6853346.84
#Sta/Elev= 30
  3984.1 1784.83    4474 1778.84    4764 1771.01    4854 1770.01    4934 1770.46
  5004.4 1769.18  5034.4  1771.4  5044.5 1771.24  5064.7 1767.98  5078.3 1767.97
  5078.8 1767.47  5091.4 1767.97  5133.6 1768.89  5169.6    1771  5256.6 1770.06
    5297 1771.26  5453.1 1771.53  5746.7 1775.61  5761.6  1776.6  5771.7 1775.96
  5807.4 1776.81  5832.3 1779.63  5862.6 1780.14  5875.8 1782.85  5878.3 1783.45
  5883.3 1782.53  5894.9 1784.09  5933.3 1786.33  5981.3 1787.03  6146.6 1789.67
#Mann= 8 ,-1 , 0
  3984.1     .07       0  5078.3     .07       0  5091.4     .07       0
  5133.6    .035       0  5746.7     .07       0  5875.8    .125       0
  5894.9    .063       0  5981.3    .094       0
Bank Sta=5078.3,5091.4
XS Rating Curve= 0 ,0
Exp/Cntr=0.3,0.1

Type RM Length L Ch R = 1 ,32090   ,369,369,369
BEGIN DESCRIPTION:
Indian Creek 32089.63
END DESCRIPTION:
XS GIS Cut Line= 3
      1547157.29      6855591.65      1547355.21      6854424.94
      1547422.82      6853431.62
#Sta/Elev= 30
  3830.2 1785.42    4245 1781.13  4604.6 1775.77  4888.8 1769.66  4939.5 1769.49
  4983.6 1767.05  4984.1 1766.55  4996.8 1767.05  5040.6 1768.16  5100.7 1767.59
  5160.9 1768.34  5180.9 1769.78  5291.2 1769.11  5352.9 1769.65  5552.7 1772.49
  5601.9 1774.14    5662 1774.84  5712.1 1776.93  5732.2 1776.31  5762.2 1777.59
  5778.5 1777.42  5792.3  1778.7  5802.3  1782.8  5818.9 1785.05  5823.9 1784.31
  5832.4 1785.27  5902.6 1786.61  5922.6 1788.68  5932.6 1788.97  6009.2 1789.68
#Mann= 8 ,-1 , 0
  3830.2     .07       0    4245    .035       0  4604.6     .07       0
  4983.6     .07       0  4996.8     .07       0  5352.9    .035       0
  5552.7     .07       0  5778.5    .063       0
Bank Sta=4983.6,4996.8
XS Rating Curve= 0 ,0
Exp/Cntr=0.3,0.1

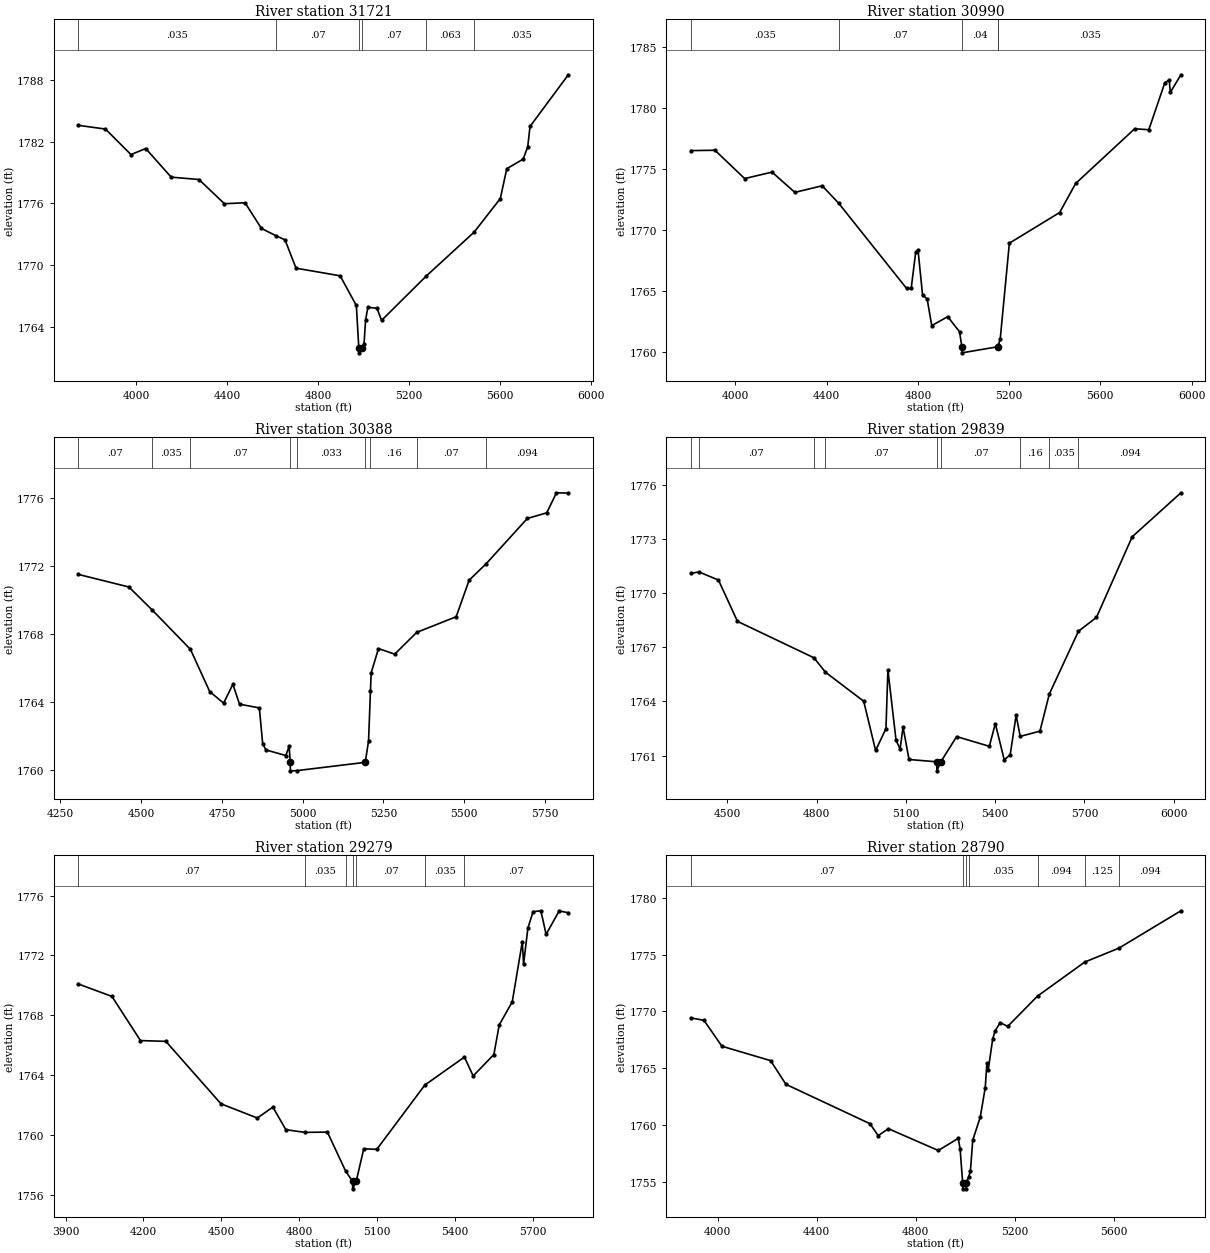
Type RM Length L Ch R = 1 ,31721   ,731,731,731
BEGIN DESCRIPTION:
Indian Creek 31720.86
END DESCRIPTION:
XS GIS Cut Line= 3
      1547438.55      6855529.07       1547662.5      6854294.73
      1547730.11      6853400.27
#Sta/Elev= 30
  3747.4 1783.58  3866.5 1783.22  3978.4 1780.74  4043.2 1781.33    4155 1778.55
    4277 1778.32  4388.8 1775.97  4479.4 1776.06  4551.4 1773.57  4616.1 1772.85
  4654.9 1772.46  4703.3 1769.71  4896.9 1768.97  4968.1 1766.09  4978.9 1761.99
  4979.4 1761.49  4992.2 1761.99  5001.9 1762.34  5008.6 1764.66  5018.7 1765.91
  5058.8 1765.82  5078.8 1764.64  5275.8 1768.96  5485.3 1773.21  5600.3 1776.47
  5628.7 1779.37  5700.6  1780.3  5720.7 1781.49  5730.7 1783.47  5898.9 1788.49
#Mann= 6 ,-1 , 0
  3747.4    .035       0  4616.1     .07       0  4978.9     .07       0
  4992.2     .07       0  5275.8    .063       0  5485.3    .035       0
Bank Sta=4978.9,4992.2
XS Rating Curve= 0 ,0
Exp/Cntr=0.3,0.1

Type RM Length L Ch R = 1 ,30990   ,602,602,602
BEGIN DESCRIPTION:
Indian Creek 30990.24
END DESCRIPTION:
XS GIS Cut Line= 3
      1548240.63       6855383.3      1548209.38      6854185.36
      1548146.88      6853237.47
#Sta/Elev= 30
  3804.9 1776.52  3910.2 1776.55  4040.3 1774.23  4160.3 1774.76  4260.4  1773.1
  4380.4 1773.64  4452.6 1772.21  4750.5 1765.23  4770.5 1765.23  4790.5 1768.23
  4800.5 1768.38  4820.5 1764.69  4840.6 1764.37  4860.6 1762.19  4930.6 1762.92
  4982.5 1761.69  4992.7 1760.46  4993.2 1759.96  5150.9 1760.46  5153.2 1760.61
    5161 1761.11    5201 1768.94  5421.5 1771.45  5491.7 1773.83  5750.5 1778.31
  5812.4 1778.23  5882.5 1782.07  5901.7 1782.31  5906.7 1781.29  5953.2 1782.73
#Mann= 5 ,-1 , 0
  3804.9    .035       0  4452.6     .07       0  4992.7     .04       0
  5150.9     .07       0  5153.2    .035       0
Bank Sta=4992.7,5150.9
XS Rating Curve= 0 ,0
Exp/Cntr=0.3,0.1

Type RM Length L Ch R = 1 ,30388   ,549,549,549
BEGIN DESCRIPTION:
Indian Creek 30358.05
END DESCRIPTION:
XS GIS Cut Line= 4
      1548568.86      6855004.42      1548569.57      6854606.19
      1548686.04      6854079.87      1548713.68      6853501.31
#Sta/Elev= 30
  4305.7 1771.51  4462.1 1770.77  4534.7 1769.41  4652.7  1767.1  4712.3 1764.62
  4755.3 1763.94    4784 1765.05  4804.5 1763.88  4865.9 1763.66  4876.2 1761.56
  4886.2 1761.19  4947.9 1760.86  4958.1 1761.41  4961.5 1760.46    4962 1759.96
  4980.9 1759.97  5193.7 1760.46  5203.9 1761.72  5209.8 1764.63    5212 1765.72
  5234.7 1767.15  5284.9 1766.82  5352.8  1768.1  5475.1 1769.02  5515.2 1771.17
  5567.6 1772.13  5695.4  1774.8  5755.4 1775.13  5785.5 1776.31  5822.2 1776.29
#Mann= 9 ,-1 , 0
  4305.7     .07       0  4534.7    .035       0  4652.7     .07       0
  4961.5    .033       0  4980.9    .033       0  5193.7     .07       0
  5209.8     .16       0  5352.8     .07       0  5567.6    .094       0
Bank Sta=4961.5,5193.7
XS Rating Curve= 0 ,0
Exp/Cntr=0.3,0.1

Type RM Length L Ch R = 1 ,29839   ,560,560,560
BEGIN DESCRIPTION:
Indian Creek 8.0
END DESCRIPTION:
XS GIS Cut Line= 3
       1548780.3      6855237.21      1548959.55      6854569.98
      1548961.86      6853614.17
#Sta/Elev= 30
  4377.5  1771.1  4404.3 1771.18  4469.9 1770.73  4533.8 1768.44  4790.8 1766.42
  4829.5 1765.62  4958.1 1764.01  4998.1 1761.28  5032.9 1762.49  5039.4 1765.75
  5066.8 1761.84  5080.4 1761.37  5090.4 1762.57  5110.4 1760.78  5203.5 1760.65
    5204 1760.15  5217.2 1760.65  5270.4 1762.05  5380.4 1761.51  5400.4 1762.77
  5430.4 1760.76  5450.4 1761.04  5470.4 1763.24    5484 1762.06  5550.4 1762.35
  5581.9 1764.41  5679.8 1767.89  5740.4 1768.66  5860.4 1773.13  6024.2 1775.57
#Mann= 9 ,-1 , 0
  4377.5    .035       0  4404.3     .07       0  4790.8    .035       0
  4829.5     .07       0  5203.5     .07       0  5217.2     .07       0
    5484     .16       0  5581.9    .035       0  5679.8    .094       0
Bank Sta=5203.5,5217.2
XS Rating Curve= 0 ,0
Exp/Cntr=0.3,0.1

Type RM Length L Ch R = 1 ,29279   ,489,489,489
BEGIN DESCRIPTION:
Indian Creek 29279.05
END DESCRIPTION:
XS GIS Cut Line= 3
      1549286.11      6855337.37      1549329.17      6854284.32
        1549406.      6853452.79
#Sta/Elev= 30
  3948.9 1770.09  4078.4 1769.26  4188.5 1766.31  4286.2 1766.26  4498.7 1762.09
  4638.8 1761.14  4698.9 1761.87  4748.9 1760.36  4823.3 1760.18  4909.1  1760.2
  4979.2  1757.6  5006.1 1756.91  5006.6 1756.41    5020 1756.91  5049.3 1759.08
  5099.6 1759.05  5284.7 1763.34  5437.3 1765.21  5471.1 1763.95  5550.9 1765.38
  5571.6 1767.36  5621.8  1768.9  5660.5 1772.91  5665.5 1771.42    5682 1773.82
  5702.1 1774.92  5732.2 1774.98  5752.3  1773.4  5802.5 1774.97  5837.9 1774.85
#Mann= 7 ,-1 , 0
  3948.9     .07       0  4823.3    .035       0  4979.2     .07       0
  5006.1     .07       0    5020     .07       0  5284.7    .035       0
  5437.3     .07       0
Bank Sta=5006.1,5020
XS Rating Curve= 0 ,0
Exp/Cntr=0.3,0.1

Type RM Length L Ch R = 1 ,28790   ,581,581,581
BEGIN DESCRIPTION:
Indian Creek 28789.81
END DESCRIPTION:
XS GIS Cut Line= 3
      1549503.56      6855358.92       1549787.5      6854289.52
       1549907.3      6853424.94
#Sta/Elev= 30
  3892.4 1769.43  3945.1 1769.21  4017.5 1766.93  4214.1 1765.66  4276.2 1763.57
  4615.7  1760.1  4648.6 1759.05    4690 1759.66  4891.7 1757.74  4972.1 1758.81
  4979.7 1757.89  4990.1 1754.86  4990.6 1754.36  5003.5 1754.36    5004 1754.86
  5013.7 1755.39  5021.3 1755.92  5030.7 1758.65    5061 1760.67  5081.2 1763.28
  5088.1 1765.47  5093.1 1764.82  5111.4 1767.57  5121.5  1768.3  5141.7 1769.01
    5172 1768.68  5292.4 1771.35  5483.2 1774.35  5621.6 1775.58  5871.7 1778.87
#Mann= 7 ,-1 , 0
  3892.4     .07       0  4990.1     .07       0    5004     .07       0
  5013.7    .035       0  5292.4    .094       0  5483.2    .125       0
  5621.6    .094       0
Bank Sta=4990.1,5004
XS Rating Curve= 0 ,0
Exp/Cntr=0.3,0.1

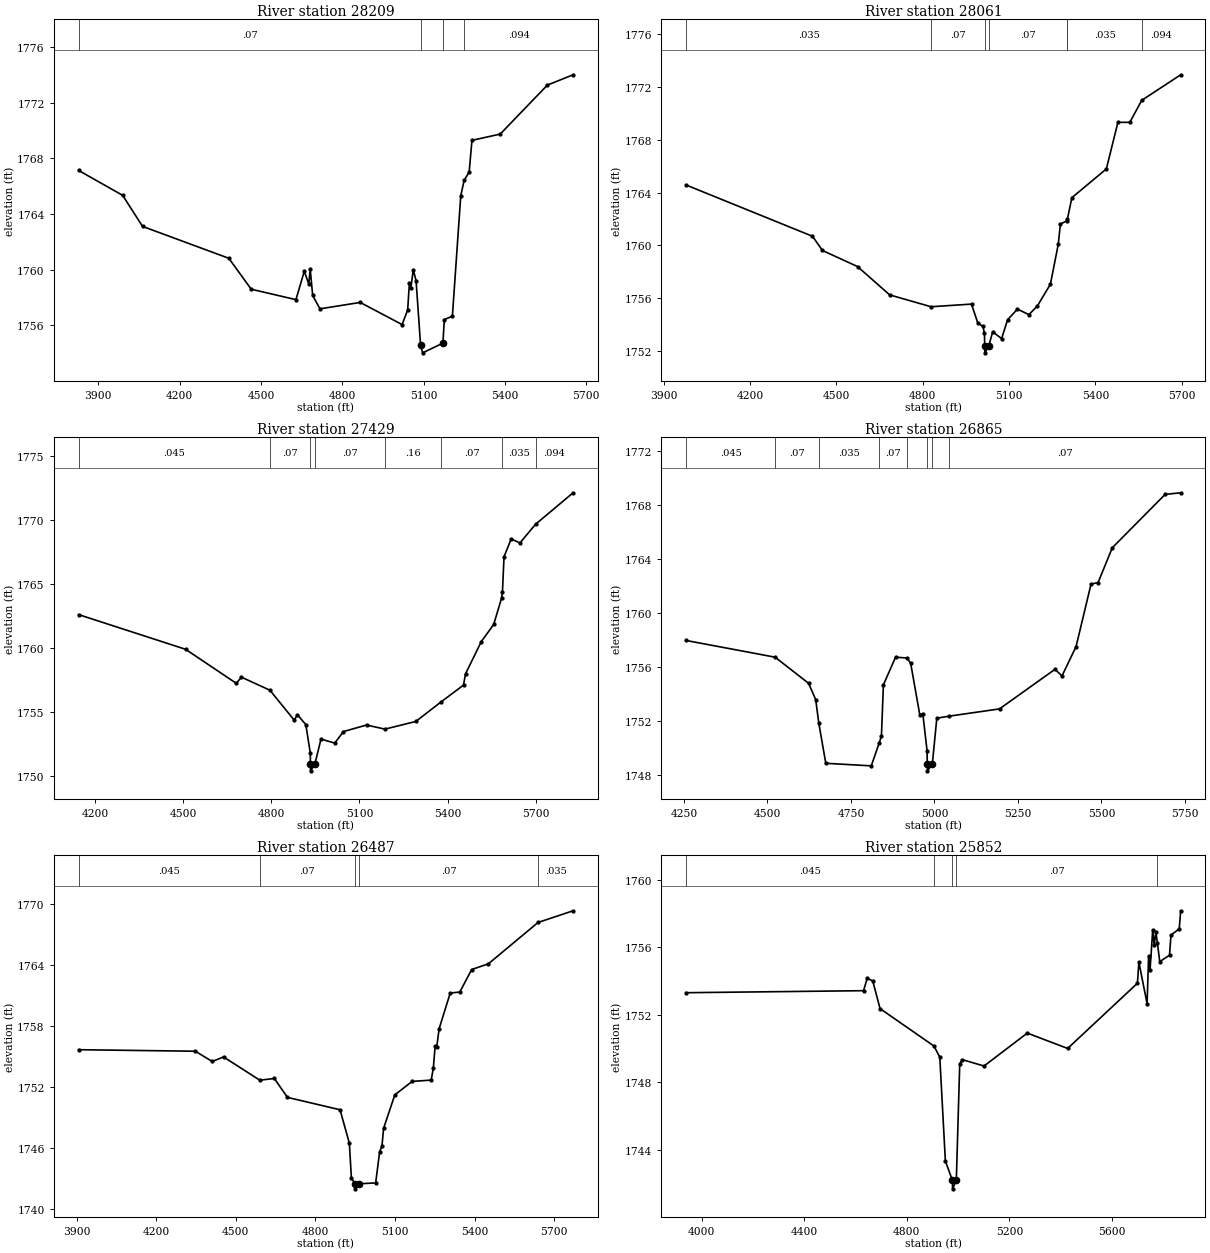
Type RM Length L Ch R = 1 ,28209   ,148,148,148
BEGIN DESCRIPTION:
Indian Creek 28300.05
END DESCRIPTION:
XS GIS Cut Line= 3
      1549969.48      6855472.85      1550285.14      6854210.21
      1550411.94      6853703.02
#Sta/Elev= 30
    3827 1767.13  3989.7 1765.34    4063 1763.11  4381.4 1760.82  4463.8  1758.6
  4628.8 1757.85  4659.7 1759.89  4676.3 1758.97  4681.5 1760.04  4690.6 1758.15
  4717.5 1757.19  4865.9 1757.65  5020.5 1756.06  5041.1 1757.12  5047.4 1759.07
  5052.5 1758.67  5061.7 1759.98    5072 1759.22  5088.6 1754.59  5096.4 1754.03
  5171.1 1754.73  5176.2 1756.42    5206 1756.66  5236.9 1765.32  5249.3 1766.41
  5267.9 1767.02  5278.2 1769.29  5382.4 1769.74  5556.5 1773.26  5651.3    1774
#Mann= 4 ,-1 , 0
    3827     .07       0  5088.6    .045       0  5171.1     .07       0
  5249.3    .094       0
Bank Sta=5088.6,5171.1
XS Rating Curve= 0 ,0
Exp/Cntr=0.3,0.1

Type RM Length L Ch R = 1 ,28061   ,632,632,632
BEGIN DESCRIPTION:
Indian Creek 27957.32
END DESCRIPTION:
XS GIS Cut Line= 3
      1550225.41      6855294.66      1550383.81      6854374.96
      1550588.34      6853617.43
#Sta/Elev= 30
  3978.3 1764.57    4417 1760.68  4451.8  1759.6  4573.6 1758.38  4685.2 1756.23
  4828.9 1755.33  4969.5 1755.53  4991.3  1754.1  5009.4 1753.83  5014.6  1753.3
  5015.3 1752.33  5015.8 1751.83  5029.3 1752.33    5043 1753.43  5074.1 1752.91
  5094.8 1754.34  5129.1 1755.15    5169 1754.73  5198.4 1755.39  5243.6 1757.04
  5270.9 1760.07  5278.3 1761.61  5299.9 1761.84  5302.8    1762  5318.2 1763.61
  5437.9 1765.79  5478.1 1769.33  5519.5 1769.33  5560.9    1771  5696.2 1772.94
#Mann= 7 ,-1 , 0
  3978.3    .035       0  4828.9     .07       0  5015.3     .07       0
  5029.3     .07       0  5299.9    .094       0  5302.8    .035       0
  5560.9    .094       0
Bank Sta=5015.3,5029.3
XS Rating Curve= 0 ,0
Exp/Cntr=0.3,0.1

Type RM Length L Ch R = 1 ,27429   ,564,564,564
BEGIN DESCRIPTION:
Indian Creek 27428.89
END DESCRIPTION:
XS GIS Cut Line= 3
      1551318.79      6855157.15      1550964.59      6854372.86
      1550662.52      6853607.26
#Sta/Elev= 30
  4143.9  1762.6    4508 1759.89  4680.8 1757.23  4698.4 1757.71  4795.3 1756.69
  4878.1 1754.35  4888.9 1754.77  4917.5 1754.01    4933 1751.75  4933.1 1750.89
  4933.6 1750.39  4948.1 1750.89  4969.2 1752.87    5016 1752.56  5045.8 1753.46
  5124.3 1753.97  5187.1 1753.65    5292 1754.25  5378.8 1755.79  5454.4 1757.09
  5461.2 1757.97    5515 1760.49  5557.2 1761.83    5584 1763.89    5587 1764.39
  5592.4 1767.12  5616.7 1768.51  5646.5  1768.2  5699.7 1769.66  5827.5 1772.12
#Mann= 8 ,-1 , 0
  4143.9    .045       0  4795.3     .07       0  4933.1     .07       0
  4948.1     .07       0  5187.1     .16       0  5378.8     .07       0
    5584    .035       0  5699.7    .094       0
Bank Sta=4933.1,4948.1
XS Rating Curve= 0 ,0
Exp/Cntr=0.3,0.1

Type RM Length L Ch R = 1 ,26865   ,378,378,378
BEGIN DESCRIPTION:
Indian Creek 26841.64
END DESCRIPTION:
XS GIS Cut Line= 3
      1551775.91      6854644.48      1551410.39       6854074.3
      1550961.43      6853408.27
#Sta/Elev= 30
  4256.6 1757.96  4522.9 1756.72  4623.1 1754.78  4644.4 1753.57  4653.4 1751.86
  4674.6 1748.84  4810.8 1748.65  4834.5 1750.35  4841.2 1750.87  4847.1 1754.67
  4883.5 1756.72  4917.8 1756.66  4928.7 1756.27    4956 1752.44    4965 1752.53
  4977.7 1749.79  4978.5 1748.78    4979 1748.28  4993.5 1748.78    5007 1752.19
  5043.6 1752.34  5194.7 1752.88  5360.7 1755.82  5381.8 1755.33  5423.9 1757.51
  5468.7 1762.15  5489.7 1762.26  5532.4 1764.85  5690.6 1768.81  5737.1 1768.93
#Mann= 8 ,-1 , 0
  4256.6    .045       0  4522.9     .07       0  4653.4    .035       0
  4834.5     .07       0  4917.8     .16       0  4978.5     .07       0
  4993.5     .16       0  5043.6     .07       0
#XS Ineff= 2 , 0
       0    4900    1756               0
Permanent Ineff=
       F       F
Bank Sta=4978.5,4993.5
XS Rating Curve= 0 ,0
Exp/Cntr=0.3,0.1

Type RM Length L Ch R = 1 ,26487   ,635,635,635
BEGIN DESCRIPTION:
Indian Creek 26491.9
END DESCRIPTION:
XS GIS Cut Line= 3
      1552398.51      6854435.59       1551594.8      6853727.02
      1550939.63      6853280.71
#Sta/Elev= 30
  3907.1 1755.64  4347.3 1755.49  4410.9 1754.48  4453.5 1754.93  4590.3 1752.64
    4645 1752.81  4694.5 1750.95  4892.8 1749.73  4927.9 1746.43  4935.5 1743.01
  4948.8 1742.45  4949.3 1741.95  4963.9 1742.45    5027 1742.53  5041.9 1745.57
  5050.8 1746.17  5056.9  1747.9  5099.3  1751.2  5164.6 1752.52  5236.4 1752.65
  5244.5 1753.85  5251.3 1756.01  5257.4 1755.94  5266.3 1757.71  5308.2 1761.22
  5344.2 1761.31  5388.9 1763.53  5451.9 1764.09  5639.1 1768.16  5771.3 1769.31
#Mann= 5 ,-1 , 0
  3907.1    .045       0  4590.3     .07       0  4948.8     .07       0
  4963.9     .07       0  5639.1    .035       0
Bank Sta=4948.8,4963.9
XS Rating Curve= 0 ,0
Exp/Cntr=0.3,0.1

Type RM Length L Ch R = 1 ,25852   ,407,407,407
BEGIN DESCRIPTION:
Indian Creek 25852.03
END DESCRIPTION:
XS GIS Cut Line= 3
      1552969.81      6854320.79      1552167.71      6853602.02
      1551419.99      6853193.02
#Sta/Elev= 30
  3939.2 1753.31  4631.2 1753.43  4645.4 1754.16  4667.1 1754.01  4695.5 1752.37
  4906.2 1750.15  4928.7 1749.49  4950.4 1743.35    4978  1742.2  4978.5  1741.7
  4993.1  1742.2  5006.5  1749.1  5016.2 1749.35  5101.2 1748.97  5270.1 1750.92
  5427.5 1750.01  5699.7 1753.87  5705.4 1755.12  5737.4 1752.66  5743.3 1755.46
    5749 1754.66  5759.4 1757.03  5765.1 1756.13  5771.6  1756.9  5777.5 1756.26
  5786.9 1755.15  5824.9 1755.53  5830.6 1756.72  5862.8 1757.09  5868.5 1758.16
#Mann= 5 ,-1 , 0
  3939.2    .045       0  4906.2     .07       0    4978     .07       0
  4993.1     .07       0  5777.5    .063       0
Bank Sta=4978,4993.1
XS Rating Curve= 0 ,0
Exp/Cntr=0.3,0.1

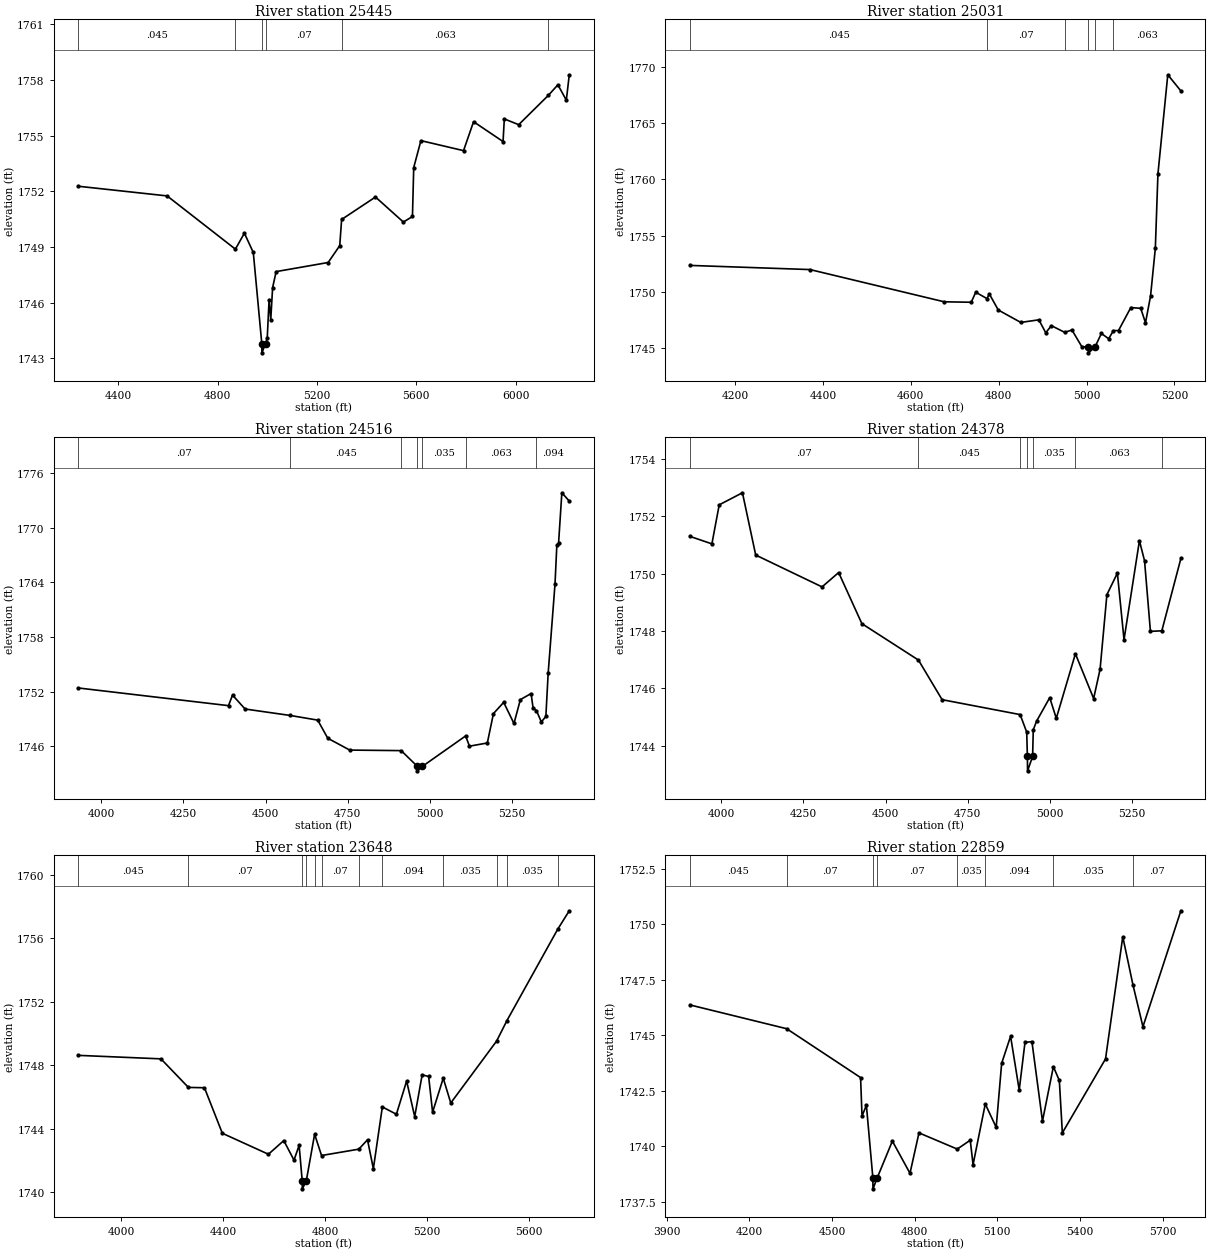
Type RM Length L Ch R = 1 ,25445   ,414,414,414
BEGIN DESCRIPTION:
Indian Creek 7.0
END DESCRIPTION:
XS GIS Cut Line= 3
       1552990.9       6853925.9      1552341.46      6853193.15
      1551353.23      6853056.95
#Sta/Elev= 30
  4239.1 1752.27  4596.3 1751.75  4871.3 1748.88  4907.5 1749.74  4943.4  1748.7
  4977.6 1743.79  4978.1 1743.29  4992.8 1743.79  4999.5 1744.08    5007 1746.16
  5013.7 1745.08  5021.2 1746.81  5035.4 1747.67  5244.9 1748.16  5291.5 1749.07
  5299.1 1750.48  5435.4 1751.69  5547.8 1750.34  5584.3 1750.64  5589.4 1753.28
  5618.4 1754.73    5790 1754.19  5830.4 1755.75  5949.1 1754.68  5954.2  1755.9
  6012.1 1755.59  6131.5 1757.17    6170 1757.74  6203.9 1756.91  6215.8 1758.28
#Mann= 6 ,-1 , 0
  4239.1    .045       0  4871.3     .07       0  4977.6     .07       0
  4992.8     .07       0  5299.1    .063       0  6131.5    .094       0
Bank Sta=4977.6,4992.8
XS Rating Curve= 0 ,0
Exp/Cntr=0.3,0.1

Type RM Length L Ch R = 1 ,25031   ,515,515,515
BEGIN DESCRIPTION:
Indian Creek 25343.4
END DESCRIPTION:
XS GIS Cut Line= 3
      1553030.15      6854011.98      1552846.61      6853207.44
        1552717.      6852945.91
#Sta/Elev= 30
  4097.6 1752.35  4370.8 1751.98  4676.1 1749.12  4737.6 1749.08  4747.9 1749.97
  4773.6  1749.4  4778.6 1749.83  4799.2 1748.39  4850.4 1747.29  4891.5 1747.52
  4907.2 1746.37    4920    1747  4950.4 1746.41  4966.8 1746.62  4989.2 1745.14
  5003.9 1745.09  5004.4 1744.59  5019.1 1745.09  5033.8 1746.31  5050.4 1745.84
  5061.1 1746.56  5072.8 1746.57  5100.8 1748.61  5123.3 1748.54  5134.2 1747.26
  5145.7 1749.63  5156.6 1753.88  5162.5 1760.47  5184.9 1769.27  5214.7 1767.84
#Mann= 6 ,-1 , 0
  4097.6    .045       0  4773.6     .07       0  4950.4    .035       0
  5003.9    .035       0  5019.1    .035       0  5061.1    .063       0
Bank Sta=5003.9,5019.1
XS Rating Curve= 0 ,0
Exp/Cntr=0.3,0.1

Type RM Length L Ch R = 1 ,24516   ,138,138,138
BEGIN DESCRIPTION:
Indian Creek 24549.41
END DESCRIPTION:
XS GIS Cut Line= 5
      1553075.07      6854080.58      1553163.85      6853449.24
       1553292.7       6853194.8      1553301.33      6852952.28
      1553209.59      6852636.26
#Sta/Elev= 30
  3930.2 1752.39  4387.2 1750.45  4399.4 1751.61  4437.7 1750.08  4575.5 1749.37
  4658.8 1748.86  4689.4 1746.87  4756.3 1745.57    4913 1745.51  4961.9 1743.79
  4962.4 1743.29  4977.8 1743.79    5109 1747.12  5120.9    1746  5175.2 1746.35
  5193.8 1749.58    5225 1750.81  5256.3 1748.49  5275.8 1751.11  5308.4 1751.78
  5314.6 1750.17  5324.8  1749.9  5339.6 1748.66  5353.4 1749.26  5360.4 1754.01
  5381.2 1763.78  5386.9 1768.12  5392.1  1768.3  5402.1 1773.83  5424.7 1772.92
#Mann= 7 ,-1 , 0
  3930.2     .07       0  4575.5    .045       0    4913    .035       0
  4961.9    .035       0  4977.8    .035       0    5109    .063       0
  5324.8    .094       0
Bank Sta=4961.9,4977.8
XS Rating Curve= 0 ,0
Exp/Cntr=0.3,0.1

Type RM Length L Ch R = 1 ,24378   ,730,730,730
BEGIN DESCRIPTION:
Indian Creek 6.0
END DESCRIPTION:
XS GIS Cut Line= 5
      1553210.31      6854096.18       1553299.1      6853464.82
      1553427.95      6853210.38      1553436.59      6852967.86
      1553344.82      6852651.76
#Sta/Elev= 30
  3904.6  1751.3  3971.3 1751.04  3993.6  1752.4  4064.3 1752.82  4104.7 1750.65
  4306.7 1749.54  4357.2 1750.04  4427.9 1748.26  4600.2 1746.99  4672.2 1745.61
  4909.8 1745.09  4929.8 1744.48  4931.9 1743.63  4932.4 1743.13  4947.8 1743.63
  4949.8 1744.56  4959.8 1744.86  4999.9 1745.68  5019.9 1744.96  5078.1 1747.21
  5133.6 1745.65  5153.2 1746.67    5174 1749.27  5205.9 1750.02  5226.1  1747.7
    5273 1751.15  5288.6 1750.45  5306.5 1747.99  5341.2 1748.01  5399.2 1750.53
#Mann= 7 ,-1 , 0
  3904.6     .07       0  4600.2    .045       0  4909.8    .035       0
  4931.9    .035       0  4947.8    .035       0  5078.1    .063       0
  5341.2    .035       0
Bank Sta=4931.9,4947.8
XS Rating Curve= 0 ,0
Exp/Cntr=0.3,0.1

Type RM Length L Ch R = 1 ,23648   ,789,789,789
BEGIN DESCRIPTION:
Indian Creek 23648.17
END DESCRIPTION:
XS GIS Cut Line= 3
      1554020.26      6854300.48      1554147.35      6852989.93
      1554280.26      6852394.28
#Sta/Elev= 30
  3832.3 1748.63  4156.3 1748.41  4264.2 1746.61  4327.1 1746.59  4397.4 1743.72
  4578.3  1742.4  4638.5 1743.26  4678.7 1742.03  4698.8 1742.96  4710.9 1740.72
  4711.4 1740.22  4726.9 1740.72  4759.6 1743.66  4786.8 1742.32  4933.1 1742.72
  4967.2 1743.31  4990.2 1741.49  5025.5 1745.38  5080.6 1744.92  5120.8 1747.01
  5152.5 1744.77  5181.7  1747.4  5207.2  1747.3  5222.7 1745.05  5264.5 1747.19
  5294.1 1745.63    5474 1749.53  5514.5 1750.82    5714 1756.58  5759.3 1757.74
#Mann= 12 ,-1 , 0
  3832.3    .045       0  4264.2     .07       0  4710.9    .035       0
  4726.9     .07       0  4759.6     .16       0  4786.8     .07       0
  4933.1    .035       0  5025.5    .094       0  5264.5    .035       0
    5474     .07       0  5514.5    .035       0    5714     .07       0
Bank Sta=4710.9,4726.9
XS Rating Curve= 0 ,0
Exp/Cntr=0.3,0.1

Type RM Length L Ch R = 1 ,22859   ,720,720,720
BEGIN DESCRIPTION:
Indian Creek 22806.8
END DESCRIPTION:
XS GIS Cut Line= 3
      1554546.52      6854359.59      1554870.68       6853306.2
      1555064.96      6852656.15
#Sta/Elev= 30
  3985.2 1746.36  4335.8 1745.29    4604 1743.09  4609.2 1741.36  4625.1 1741.84
  4648.5 1738.58    4649 1738.08  4664.5 1738.58  4719.3 1740.23  4783.2 1738.78
  4815.8  1740.6  4954.7 1739.87  5001.8 1740.27    5012 1739.17  5056.3  1741.9
  5095.9 1740.85  5115.7 1743.73  5148.1 1744.95  5179.4 1742.53  5200.3 1744.67
  5225.5 1744.71  5263.8 1741.13  5303.3 1743.58  5324.9 1742.96  5335.9  1740.6
  5492.5 1743.93  5555.1 1749.43  5591.7 1747.28  5628.2 1745.38  5765.8  1750.6
#Mann= 8 ,-1 , 0
  3985.2    .045       0  4335.8     .07       0  4648.5    .035       0
  4664.5     .07       0  4954.7    .035       0  5056.3    .094       0
  5303.3    .035       0  5591.7     .07       0
Bank Sta=4648.5,4664.5
XS Rating Curve= 0 ,0
Exp/Cntr=0.3,0.1