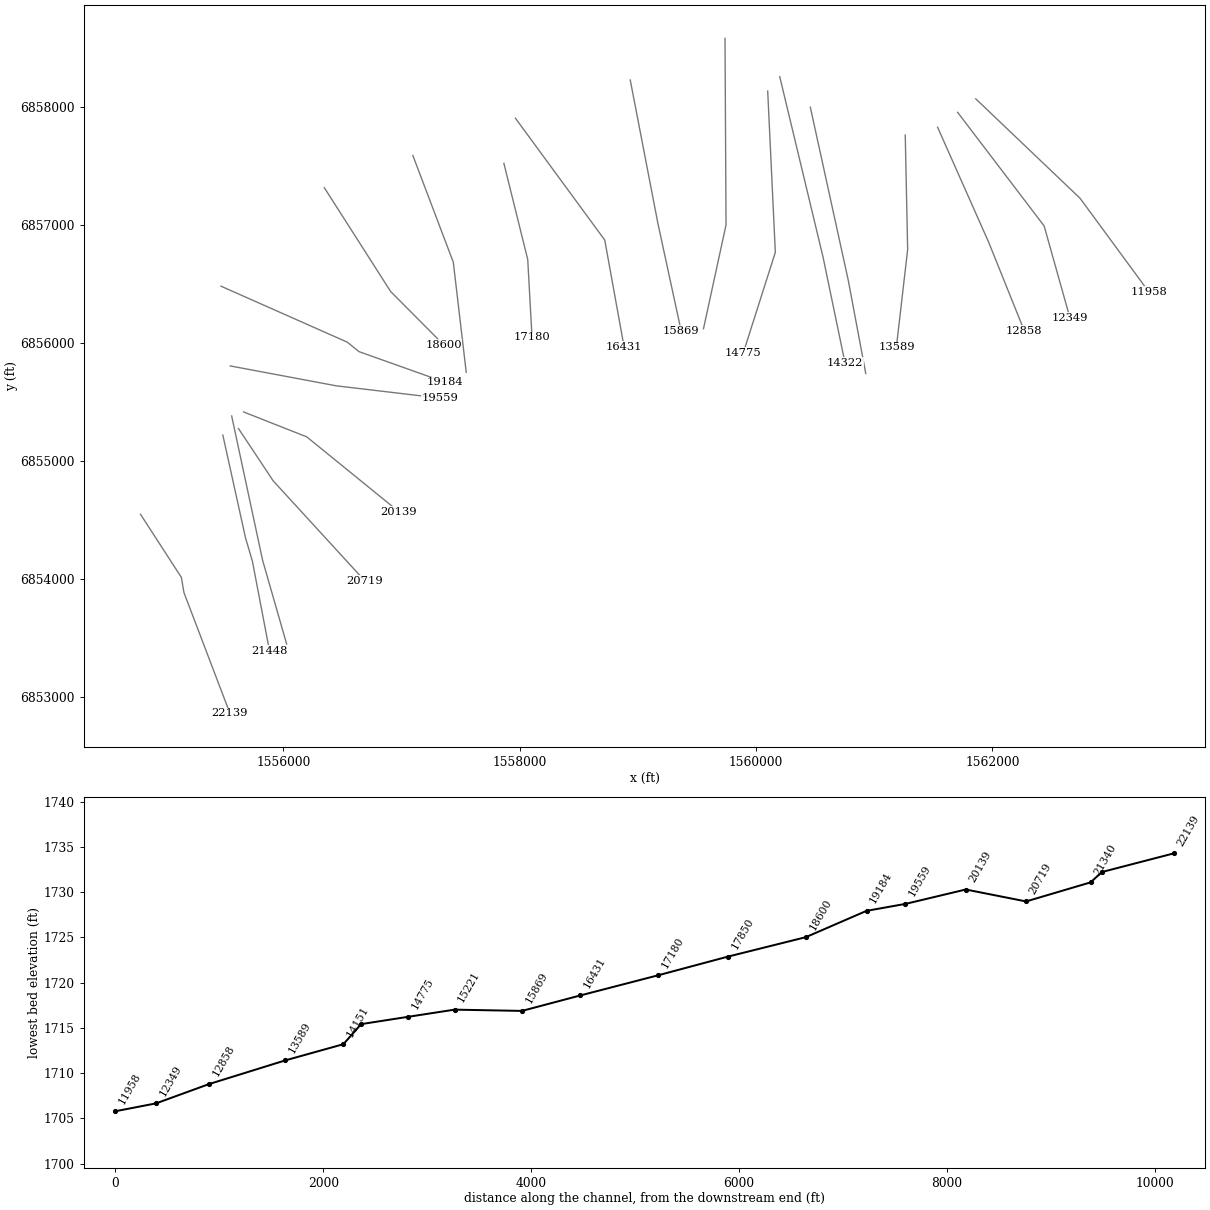
HEC-RAS study Indian Creek.prj: Indian Creek Base Level Engineering

--- Indian Creek.g01 (geometry) --- (continued)

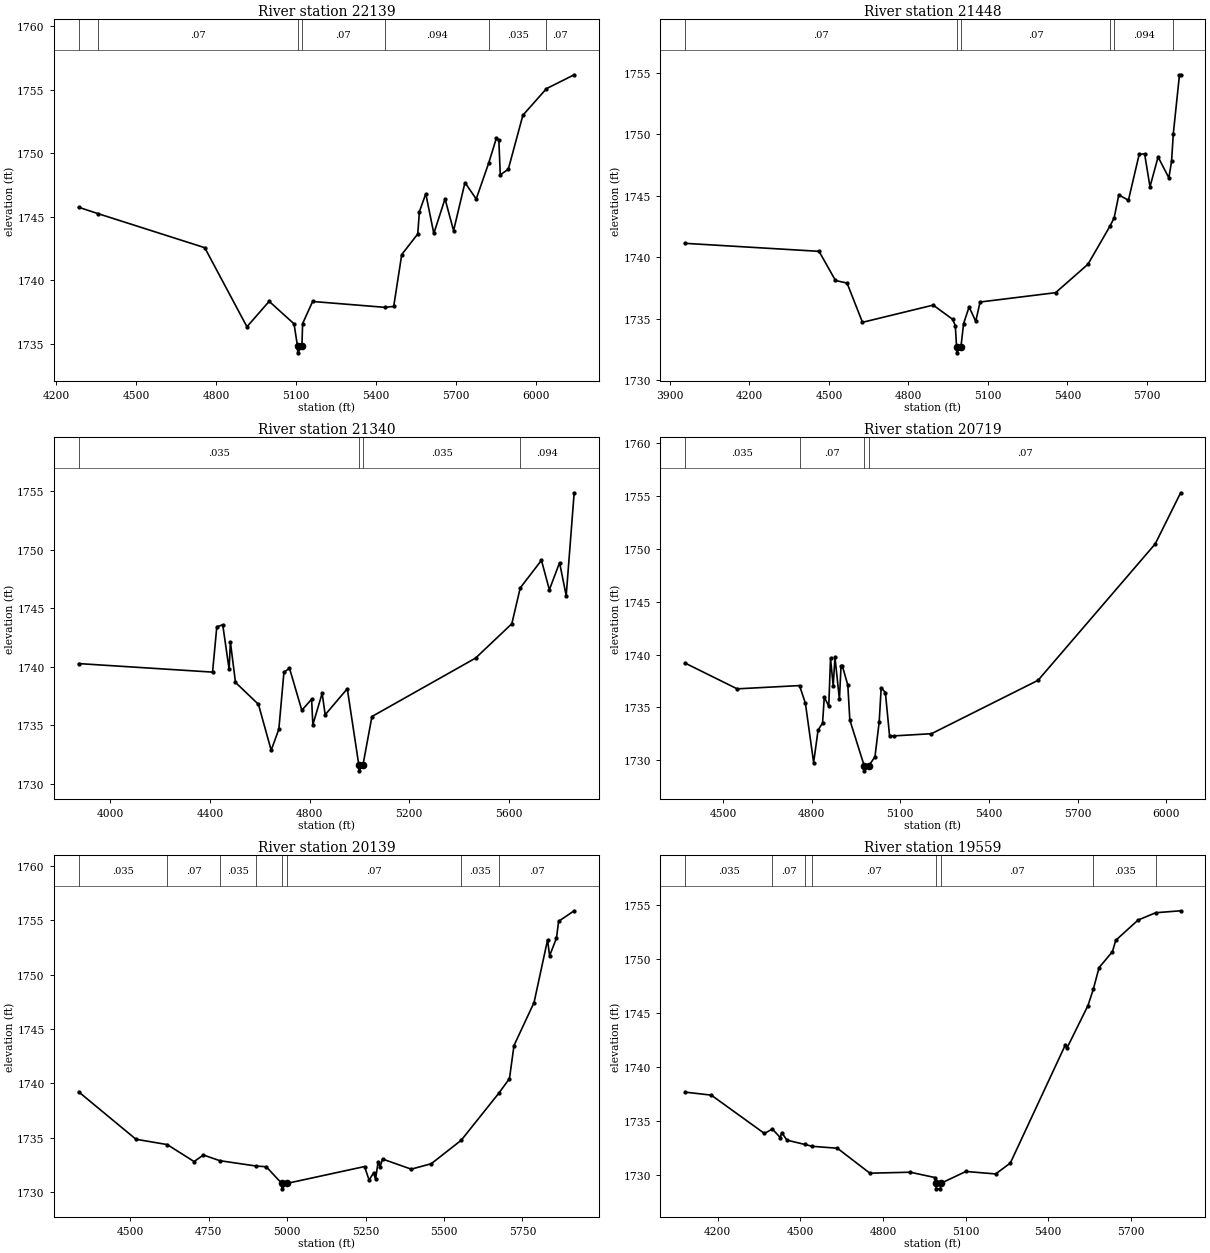
Type RM Length L Ch R = 1 ,22139   ,691,691,691
BEGIN DESCRIPTION:
Indian Creek 22004.05
END DESCRIPTION:
XS GIS Cut Line= 4
      1554792.62      6854550.37      1555138.09      6854016.14
      1555159.94      6853887.74       1555549.1       6852864.7
#Sta/Elev= 30
    4284 1745.74  4358.1 1745.23  4757.6 1742.56  4916.1 1736.34  4999.5 1738.34
    5093 1736.57  5106.1 1734.79  5106.6 1734.29  5122.6 1734.79  5125.1 1736.59
  5162.8 1738.33  5433.3 1737.87  5467.3 1737.94  5497.4 1742.02  5557.6 1743.64
  5563.7 1745.39  5587.7  1746.8  5617.9 1743.68    5660  1746.4  5692.1  1743.9
  5734.9 1747.68  5777.1 1746.39  5824.4 1749.24  5852.6 1751.16  5862.1 1751.02
  5867.5 1748.29  5897.6 1748.73  5952.4 1752.98    6041 1755.07    6145 1756.16
#Mann= 7 ,-1 , 0
    4284    .045       0  4358.1     .07       0  5106.1     .07       0
  5122.6     .07       0  5433.3    .094       0  5824.4    .035       0
    6041     .07       0
Bank Sta=5106.1,5122.6
XS Rating Curve= 0 ,0
Exp/Cntr=0.3,0.1

Type RM Length L Ch R = 1 ,21448   ,108,108,108
BEGIN DESCRIPTION:
Indian Creek 21484.62
END DESCRIPTION:
XS GIS Cut Line= 4
       1555488.8      6855221.77      1555680.53      6854352.14
      1555738.85      6854154.02      1555883.83      6853394.38
#Sta/Elev= 30
  3957.1 1741.13  4462.7 1740.48  4524.7 1738.11  4568.4  1737.9  4626.6 1734.71
  4893.6 1736.11  4966.6 1734.96    4977 1734.44  4981.7 1732.73  4982.2 1732.23
  4998.3 1732.73  5008.3 1734.61  5029.1 1735.96  5054.1 1734.79  5070.5 1736.36
  5355.5 1737.12  5477.7 1739.43  5561.1 1742.54  5576.5  1743.2  5594.2 1745.07
  5630.4 1744.63  5671.1 1748.37  5691.5  1748.4  5711.8 1745.73  5742.4 1748.15
  5783.1 1746.45  5793.3 1747.81  5799.8 1750.04  5823.1 1754.83  5827.5 1754.83
#Mann= 6 ,-1 , 0
  3957.1     .07       0  4981.7     .07       0  4998.3     .07       0
  5561.1    .035       0  5576.5    .094       0  5799.8    .063       0
Bank Sta=4981.7,4998.3
XS Rating Curve= 0 ,0
Exp/Cntr=0.3,0.1

Type RM Length L Ch R = 1 ,21340   ,621,621,621
BEGIN DESCRIPTION:
Indian Creek 21060.9
END DESCRIPTION:
XS GIS Cut Line= 3
      1555563.55      6855383.28      1555825.15      6854161.89
       1556028.7      6853451.78
#Sta/Elev= 30
  3873.7 1740.27  4410.9 1739.54    4428 1743.42  4451.8 1743.59  4477.4 1739.77
  4482.5 1742.11  4502.9 1738.66    4595 1736.78  4646.1 1732.85  4676.8 1734.65
  4697.2 1739.52  4719.5 1739.88    4769 1736.27  4808.2 1737.22  4813.3 1735.04
  4850.6 1737.73  4862.7 1735.89  4951.4 1738.12  4997.6 1731.59  4998.1 1731.09
  5014.2 1731.59  5050.3 1735.74    5466 1740.74  5611.4 1743.68  5645.2 1746.75
  5730.2 1749.11    5762 1746.59    5803 1748.91  5829.5 1746.08  5861.5 1754.89
#Mann= 4 ,-1 , 0
  3873.7    .035       0  4997.6    .035       0  5014.2    .035       0
  5645.2    .094       0
Bank Sta=4997.6,5014.2
XS Rating Curve= 0 ,0
Exp/Cntr=0.3,0.1

Type RM Length L Ch R = 1 ,20719   ,580,580,580
BEGIN DESCRIPTION:
Indian Creek 5.0
END DESCRIPTION:
XS GIS Cut Line= 3
      1555620.97      6855277.37      1555914.74      6854833.87
      1556687.83      6853989.49
#Sta/Elev= 30
  4371.9 1739.19  4548.1 1736.75  4759.1 1737.06    4779 1735.38  4806.8 1729.76
  4821.9 1732.85    4837  1733.5  4842.9 1735.97    4858  1735.1    4864 1739.63
  4873.1 1737.04    4879 1739.74  4894.1 1735.76  4899.6 1738.93  4903.9 1738.93
  4922.5  1737.1  4929.3  1733.8  4977.7 1729.48  4978.2 1728.98  4994.3 1729.48
  5014.4 1730.32  5028.6 1733.59  5035.4 1736.85  5049.6  1736.4  5063.7 1732.31
  5077.9 1732.29  5205.6  1732.5  5566.3 1737.56  5962.8 1750.49  6048.7 1755.33
#Mann= 4 ,-1 , 0
  4371.9    .035       0  4759.1     .07       0  4977.7     .07       0
  4994.3     .07       0
Bank Sta=4977.7,4994.3
XS Rating Curve= 0 ,0
Exp/Cntr=0.3,0.1

Type RM Length L Ch R = 1 ,20139   ,580,580,580
BEGIN DESCRIPTION:
Indian Creek 20138.62
END DESCRIPTION:
XS GIS Cut Line= 3
       1555665.1      6855417.13      1556198.96      6855206.19
      1556978.78      6854571.94
#Sta/Elev= 30
  4335.7 1739.22  4518.4 1734.86    4618 1734.37  4703.6 1732.81  4733.4 1733.41
  4785.5 1732.89  4900.7  1732.4  4933.7 1732.33  4982.9  1730.8  4983.4  1730.3
  4999.6  1730.8  5246.9 1732.35  5261.3 1731.11  5275.6 1731.76  5282.1  1731.2
    5290 1732.76  5296.4 1732.32  5304.2 1733.04  5395.6 1732.11  5459.5 1732.61
    5555 1734.77  5674.6 1739.09  5708.7 1740.44  5723.1 1743.48    5787 1747.43
  5830.1 1753.19  5836.6 1751.73  5858.5 1753.36  5865.3  1754.9  5914.9 1755.87
#Mann= 8 ,-1 , 0
  4335.7    .035       0    4618     .07       0  4785.5    .035       0
  4900.7     .07       0  4982.9     .07       0  4999.6     .07       0
    5555    .035       0  5674.6     .07       0
Bank Sta=4982.9,4999.6
XS Rating Curve= 0 ,0
Exp/Cntr=0.3,0.1

Type RM Length L Ch R = 1 ,19559   ,375,375,375
BEGIN DESCRIPTION:
Indian Creek 19558.58
END DESCRIPTION:
XS GIS Cut Line= 3
      1555551.44      6855807.01      1556448.96      6855638.48
      1557329.21      6855534.31
#Sta/Elev= 30
  4081.2 1737.67  4176.4 1737.39  4369.3 1733.84    4398 1734.25  4426.9 1733.46
    4432 1733.92  4451.1 1733.22  4516.5 1732.82  4543.3 1732.65  4634.3 1732.47
  4752.2 1730.16  4898.8 1730.25  4989.8 1729.75  4992.1 1729.21  4992.6 1728.71
  5008.4 1728.71  5008.9 1729.21  5101.2 1730.32  5209.1 1730.09  5262.3  1731.1
  5462.6 1742.07  5467.6 1741.73  5544.3 1745.69  5563.6  1747.2  5584.5  1749.2
  5633.3 1750.69    5645 1751.73  5726.2 1753.61  5790.3 1754.29  5880.8 1754.47
#Mann= 8 ,-1 , 0
  4081.2    .035       0    4398     .07       0  4516.5    .035       0
  4543.3     .07       0  4992.1     .07       0  5008.9     .07       0
  5563.6    .035       0  5790.3     .07       0
Bank Sta=4992.1,5008.9
XS Rating Curve= 0 ,0
Exp/Cntr=0.3,0.1

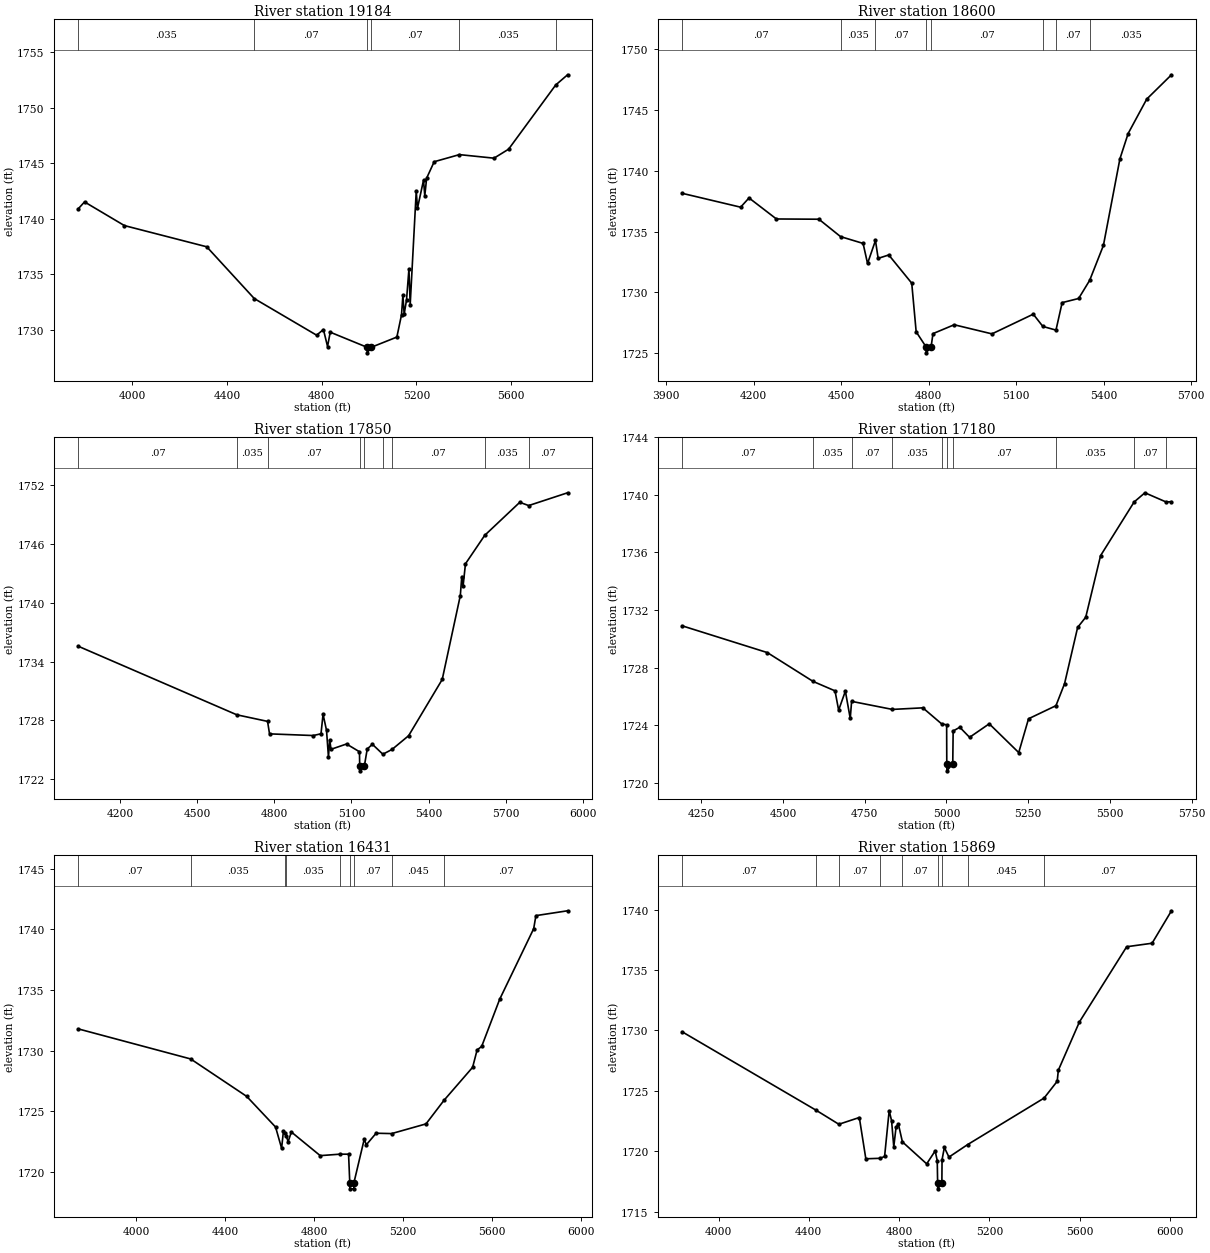
Type RM Length L Ch R = 1 ,19184   ,584,584,584
BEGIN DESCRIPTION:
Indian Creek 19276.65
END DESCRIPTION:
XS GIS Cut Line= 4
      1555473.09      6856482.39      1556541.91      6856008.11
      1556641.31      6855927.87      1557365.62      6855669.73
#Sta/Elev= 30
    3772 1740.92  3798.3 1741.53  3966.6  1739.4  4314.3 1737.49  4514.9 1732.83
  4778.2 1729.53    4807 1730.04  4824.4 1728.51  4835.7  1729.8  4991.4 1728.44
  4991.9 1727.94    5009 1728.44  5117.1 1729.36  5136.7 1731.36  5142.6 1733.12
  5147.9 1731.42  5157.9  1732.7  5168.1 1735.49  5173.4 1732.29  5198.9  1742.5
  5204.2 1740.97  5229.7 1743.49    5235 1742.08  5242.8 1743.67  5274.7 1745.15
  5381.2 1745.79  5527.3 1745.47  5588.9 1746.28  5787.8 1752.06    5838 1752.98
#Mann= 6 ,-1 , 0
    3772    .035       0  4514.9     .07       0  4991.4     .07       0
    5009     .07       0  5381.2    .035       0  5787.8     .07       0
Bank Sta=4991.4,5009
XS Rating Curve= 0 ,0
Exp/Cntr=0.3,0.1

Type RM Length L Ch R = 1 ,18600   ,750,750,750
BEGIN DESCRIPTION:
Indian Creek 18600.197
END DESCRIPTION:
XS GIS Cut Line= 3
      1556347.29      6857316.66      1556909.16      6856436.28
      1557354.97      6855988.03
#Sta/Elev= 30
  3955.6 1738.15  4155.7 1737.01  4184.5 1737.77  4278.4 1736.04    4424 1736.02
  4498.1 1734.59  4575.4 1734.03  4590.7 1732.38  4617.8 1734.27    4627  1732.8
  4663.4 1733.08  4742.1 1730.76  4757.3 1726.76  4790.9 1725.53  4791.4 1725.03
  4808.5 1725.53  4814.9 1726.61  4887.6 1727.34    5017 1726.59  5158.5 1728.21
  5191.5  1727.2  5236.4  1726.9  5257.5 1729.16    5314  1729.5  5351.8 1730.99
  5398.9 1733.86  5455.5 1740.99  5483.7 1743.07  5547.4  1745.9  5632.2  1747.9
#Mann= 8 ,-1 , 0
  3955.6     .07       0  4498.1    .035       0  4617.8     .07       0
  4790.9     .07       0  4808.5     .07       0  5191.5    .035       0
  5236.4     .07       0  5351.8    .035       0
Bank Sta=4790.9,4808.5
XS Rating Curve= 0 ,0
Exp/Cntr=0.3,0.1

Type RM Length L Ch R = 1 ,17850   ,670,670,670
BEGIN DESCRIPTION:
Indian Creek 17850.48
END DESCRIPTION:
XS GIS Cut Line= 3
      1557096.42      6857589.33      1557438.55      6856685.36
      1557547.92       6855753.1
#Sta/Elev= 30
  4036.3 1735.55  4653.4 1728.58  4773.2 1727.91  4780.9 1726.64  4951.2 1726.47
  4981.3 1726.65  4989.3 1728.63  5002.8    1727  5010.3  1724.3  5015.3 1726.03
  5020.3 1725.07  5080.7 1725.61  5131.1 1724.82    5132 1723.38  5132.5 1722.88
  5150.2 1723.38  5161.3  1725.1  5181.4 1725.58  5222.2 1724.57  5258.1 1725.06
  5322.4 1726.45  5453.3 1732.17  5523.8 1740.71  5529.5 1742.64  5534.6 1741.68
  5543.9 1743.94  5618.8 1746.83  5755.3 1750.19  5790.1 1749.86  5941.5 1751.16
#Mann= 9 ,-1 , 0
  4036.3     .07       0  4653.4    .035       0  4773.2     .07       0
    5132     .07       0  5150.2     .07       0  5222.2    .035       0
  5258.1     .07       0  5618.8    .035       0  5790.1     .07       0
Bank Sta=5132,5150.2
XS Rating Curve= 0 ,0
Exp/Cntr=0.3,0.1

Type RM Length L Ch R = 1 ,17180   ,749,749,749
BEGIN DESCRIPTION:
Indian Creek 17354.53
END DESCRIPTION:
XS GIS Cut Line= 3
      1557866.57      6857522.48      1558068.25      6856708.26
      1558104.44      6856051.38
#Sta/Elev= 30
  4191.6  1730.9    4452 1729.04  4591.6 1727.04    4659 1726.38  4670.1 1725.04
  4690.7 1726.36  4705.6 1724.46  4709.8 1725.65  4834.5 1725.09  4927.7  1725.2
  4985.4 1724.08  5000.5 1724.02  5000.9 1721.32  5001.4 1720.82  5019.2 1721.32
  5020.4 1723.59  5040.7 1723.85  5070.7 1723.15  5130.8 1724.09    5221 1722.09
    5251 1724.44  5334.9 1725.35  5361.2 1726.88  5401.2 1730.79    5426  1731.5
  5471.4 1735.78    5574 1739.51    5607 1740.15  5671.9 1739.51  5688.3 1739.53
#Mann= 10 ,-1 , 0
  4191.6     .07       0  4591.6    .035       0  4709.8     .07       0
  4834.5    .035       0  4985.4     .07       0  5000.9     .07       0
  5019.2     .07       0  5334.9    .035       0    5574     .07       0
  5671.9    .035       0
Bank Sta=5000.9,5019.2
XS Rating Curve= 0 ,0
Exp/Cntr=0.3,0.1

Type RM Length L Ch R = 1 ,16431   ,562,562,562
BEGIN DESCRIPTION:
Indian Creek 16431.08
END DESCRIPTION:
XS GIS Cut Line= 3
      1557963.96      6857905.08       1558719.8      6856872.86
      1558883.44      6855967.99
#Sta/Elev= 30
  3741.2 1731.79  4246.2 1729.31    4498 1726.22  4627.7 1723.69  4654.8 1721.94
  4663.2 1723.38  4669.7  1723.2  4675.8 1722.95  4684.1 1722.48  4698.7 1723.28
  4828.3 1721.33  4916.1 1721.45  4955.8 1721.45  4961.2 1719.09  4961.7 1718.59
  4979.3 1718.59  4979.8 1719.09  5026.1 1722.68  5035.7 1722.23  5079.6 1723.18
  5149.4 1723.15  5303.8 1723.95  5384.4 1725.89  5513.3 1728.62  5533.6 1730.06
  5553.9 1730.34    5635 1734.24  5787.7 1740.06  5797.8 1741.14  5940.1 1741.54
#Mann= 9 ,-1 , 0
  3741.2     .07       0  4246.2    .035       0  4669.7     .07       0
  4675.8    .035       0  4916.1     .07       0  4961.2     .07       0
  4979.8     .07       0  5149.4    .045       0  5384.4     .07       0
Bank Sta=4961.2,4979.8
XS Rating Curve= 0 ,0
Exp/Cntr=0.3,0.1

Type RM Length L Ch R = 1 ,15869   ,648,648,648
BEGIN DESCRIPTION:
Indian Creek 15702.656
END DESCRIPTION:
XS GIS Cut Line= 3
      1558935.44      6858228.49      1559169.28       6857014.6
      1559366.06      6856103.93
#Sta/Elev= 30
  3839.1 1729.89  4431.7  1723.4  4533.2 1722.23  4623.8 1722.79  4652.7 1719.37
  4715.6 1719.41  4735.8 1719.56  4756.1 1723.36  4766.7 1722.53  4776.5 1720.36
  4786.7 1722.01  4796.9 1722.24  4814.8 1720.77  4922.3 1718.95  4959.8 1720.02
  4969.1 1719.22  4970.8 1717.38  4971.3 1716.88  4989.6 1717.38  4990.4 1719.29
  5000.6 1720.31  5020.9 1719.51    5104 1720.55  5442.5  1724.4  5500.6 1725.79
  5505.7 1726.71  5599.1 1730.71  5808.4 1736.94    5921 1737.23    6007 1739.92
#Mann= 9 ,-1 , 0
  3839.1     .07       0  4431.7    .035       0  4533.2     .07       0
  4715.6    .035       0  4814.8     .07       0  4970.8     .07       0
  4989.6     .07       0    5104    .045       0  5442.5     .07       0
Bank Sta=4970.8,4989.6
XS Rating Curve= 0 ,0
Exp/Cntr=0.3,0.1

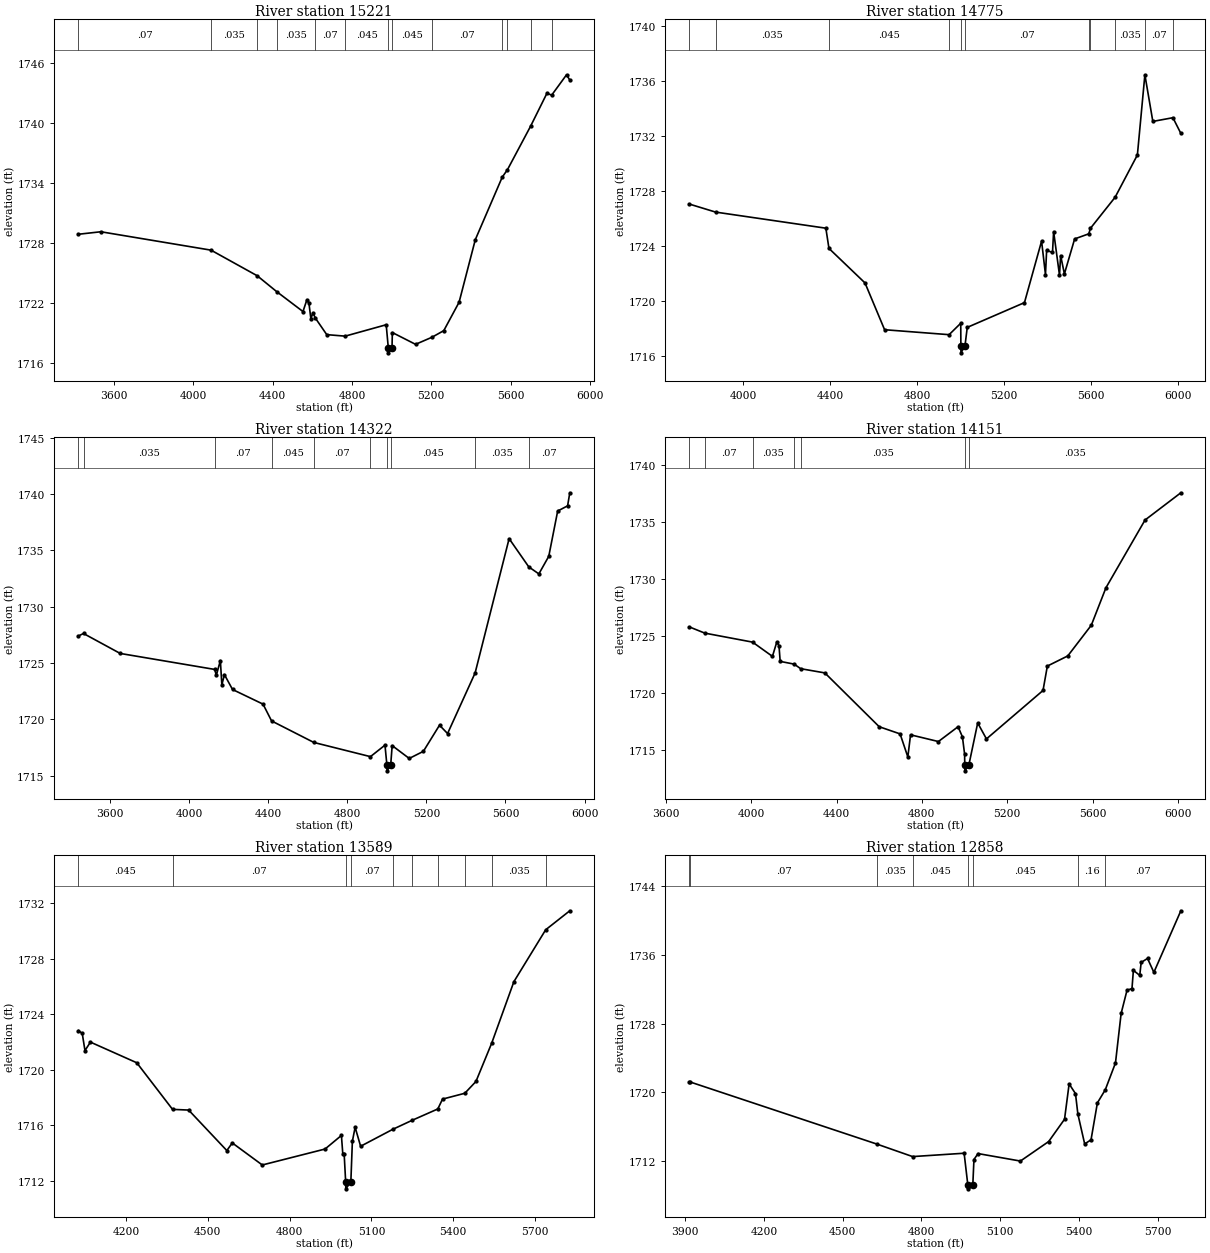
Type RM Length L Ch R = 1 ,15221   ,446,446,446
BEGIN DESCRIPTION:
Indian Creek 15220.71
END DESCRIPTION:
XS GIS Cut Line= 3
      1559737.16      6858581.22      1559745.84      6857001.33
      1559555.08        6856122.
#Sta/Elev= 30
  3419.4 1728.88  3532.6 1729.13  4088.6 1727.29  4321.6 1724.73  4419.5 1723.15
  4552.6 1721.15  4572.6 1722.34  4582.6    1722  4592.6 1720.42  4602.6 1721.03
  4615.3 1720.49  4672.6 1718.84  4765.5 1718.69  4972.6 1719.83  4983.2 1717.52
  4983.7 1717.02    5002 1717.52  5003.6 1719.05  5120.8 1717.87  5203.6 1718.58
  5263.2 1719.24  5340.4 1722.08  5422.3 1728.34  5558.1 1734.59  5584.6 1735.34
  5701.4 1739.69  5783.5 1742.97  5807.9  1742.8  5882.7 1744.83  5899.1  1744.3
#Mann= 13 ,-1 , 0
  3419.4     .07       0  4088.6    .035       0  4321.6     .07       0
  4419.5    .035       0  4615.3     .07       0  4765.5    .045       0
  4983.2    .045       0    5002    .045       0  5203.6     .07       0
  5558.1    .035       0  5584.6     .07       0  5701.4    .035       0
  5807.9     .07       0
Bank Sta=4983.2,5002
XS Rating Curve= 0 ,0
Exp/Cntr=0.3,0.1

Type RM Length L Ch R = 1 ,14775   ,453,453,453
BEGIN DESCRIPTION:
Indian Creek 3.0
END DESCRIPTION:
XS GIS Cut Line= 3
      1560098.32      6858134.77      1560162.93      6856769.53
      1559891.82      6855917.39
#Sta/Elev= 30
  3752.6 1727.04  3872.7 1726.46  4380.1 1725.29  4394.4 1723.82  4560.3 1721.31
  4650.4 1717.91  4947.2 1717.55  5000.8 1718.38  5001.4 1716.73  5001.9 1716.23
  5020.2 1716.73  5030.8 1718.08    5294 1719.88  5372.8 1724.35  5390.7 1721.92
    5396 1723.67    5423 1723.53  5428.2 1725.04  5455.2 1721.88  5460.4  1723.3
  5477.8 1721.97  5524.9 1724.51    5590 1724.88  5597.6 1725.28  5711.2 1727.54
  5813.6 1730.61  5848.1 1736.44  5884.7 1733.05  5977.1 1733.32  6013.6 1732.18
#Mann= 11 ,-1 , 0
  3752.6     .07       0  3872.7    .035       0  4394.4    .045       0
  4947.2     .07       0  5001.4     .07       0  5020.2     .07       0
    5590    .035       0  5597.6     .07       0  5711.2    .035       0
  5848.1     .07       0  5977.1    .035       0
Bank Sta=5001.4,5020.2
XS Rating Curve= 0 ,0
Exp/Cntr=0.3,0.1

Type RM Length L Ch R = 1 ,14322   ,171,171,171
BEGIN DESCRIPTION:
Indian Creek 14480.21
END DESCRIPTION:
XS GIS Cut Line= 3
      1560200.26      6858256.37      1560567.23      6856725.46
      1560752.35      6855832.52
#Sta/Elev= 30
  3439.1 1727.39  3464.8 1727.61  3650.4 1725.84  4128.9 1724.42  4136.7 1723.89
  4157.3 1725.21  4164.8 1723.05  4177.8 1723.96  4218.9 1722.64  4373.2 1721.34
  4416.4 1719.85  4630.2 1717.94  4916.6 1716.68  4990.2  1717.7    5000 1715.92
  5000.5 1715.42    5019 1715.92  5026.6 1717.66  5112.9 1716.52  5184.4 1717.15
  5266.1 1719.47  5306.9 1718.73  5446.3 1724.11  5618.3 1736.03  5717.9 1733.52
  5768.8  1732.9  5818.9 1734.46    5864 1738.48  5914.2 1738.94  5925.3  1740.1
#Mann= 10 ,-1 , 0
  3439.1     .07       0  3464.8    .035       0  4128.9     .07       0
  4416.4    .045       0  4630.2     .07       0  4916.6    .045       0
    5000    .045       0    5019    .045       0  5446.3    .035       0
  5717.9     .07       0
Bank Sta=5000,5019
XS Rating Curve= 0 ,0
Exp/Cntr=0.3,0.1

Type RM Length L Ch R = 1 ,14151   ,562,562,562
BEGIN DESCRIPTION:
Indian Creek 14084.3
END DESCRIPTION:
XS GIS Cut Line= 3
      1560458.94      6857997.87      1560780.13      6856530.82
      1560927.85      6855742.95
#Sta/Elev= 30
  3710.6 1725.82  3782.4 1725.28  4006.3 1724.49  4099.5 1723.24  4119.9  1724.5
  4130.2 1724.18  4135.8  1722.8  4201.4 1722.56  4231.8 1722.16  4345.2 1721.79
    4600 1717.07  4697.9 1716.44  4734.2 1714.42  4746.9 1716.36  4877.5 1715.77
  4969.6 1717.07  4990.1 1716.18  5000.3 1714.67  5001.1  1713.7  5001.6  1713.2
  5020.1  1713.7  5061.7  1717.4  5102.7    1716  5367.9 1720.25  5388.2 1722.39
    5484 1723.28  5594.2 1725.97  5662.9 1729.26  5846.1  1735.2    6014 1737.59
#Mann= 7 ,-1 , 0
  3710.6    .035       0  3782.4     .07       0  4006.3    .035       0
  4201.4    .045       0  4231.8    .035       0  5001.1    .035       0
  5020.1    .035       0
Bank Sta=5001.1,5020.1
XS Rating Curve= 0 ,0
Exp/Cntr=0.3,0.1

Type RM Length L Ch R = 1 ,13589   ,731,731,731
BEGIN DESCRIPTION:
Indian Creek 13588.56
END DESCRIPTION:
XS GIS Cut Line= 3
      1561261.97      6857761.99       1561282.3        6856793.
       1561186.9      6855966.19
#Sta/Elev= 30
  4025.9 1722.81  4039.9 1722.61  4049.9 1721.37  4069.9 1721.98  4239.9 1720.49
    4371 1717.13    4430 1717.08    4570 1714.16    4590 1714.71    4700 1713.12
  4930.1 1714.27  4990.1 1715.25  4995.1 1713.94  5000.1 1713.94  5005.7  1711.9
  5006.2  1711.4  5024.7  1711.9  5030.3 1714.83  5040.4 1715.84  5060.5 1714.47
  5178.3 1715.69  5249.2 1716.34  5343.5 1717.16  5360.8 1717.87  5442.4 1718.29
  5483.3 1719.14  5541.2 1721.91  5622.5 1726.34    5739 1730.08  5827.4 1731.45
#Mann= 10 ,-1 , 0
  4025.9    .045       0    4371     .07       0  5005.7     .07       0
  5024.7     .07       0  5178.3    .035       0  5249.2     .07       0
  5343.5    .035       0  5442.4     .07       0  5541.2    .035       0
    5739     .07       0
Bank Sta=5005.7,5024.7
XS Rating Curve= 0 ,0
Exp/Cntr=0.3,0.1

Type RM Length L Ch R = 1 ,12858   ,509,509,509
BEGIN DESCRIPTION:
Indian Creek 12858.11
END DESCRIPTION:
XS GIS Cut Line= 3
      1561535.58      6857828.36      1561968.06      6856853.76
      1562268.04      6856107.01
#Sta/Elev= 30
  3916.6 1721.21  3919.5 1721.21  4630.5 1713.99  4766.2 1712.54  4962.4 1712.93
  4976.3 1709.29  4976.8 1708.79  4995.5 1709.29  4999.8  1712.2  5015.4 1712.89
  5176.7 1712.02  5284.3 1714.29  5344.7 1716.88  5362.2 1720.99  5386.4 1719.86
  5395.5 1717.48  5421.4 1714.01  5445.6 1714.49  5469.8 1718.78  5499.9 1720.31
  5538.7 1723.43  5560.2 1729.18  5582.7 1731.89  5601.5 1732.07  5606.9 1734.19
  5631.1 1733.61  5636.5 1735.11  5660.7 1735.58  5684.9 1733.96  5787.6 1741.12
#Mann= 8 ,-1 , 0
  3916.6    .035       0  3919.5     .07       0  4630.5    .035       0
  4766.2    .045       0  4976.3    .035       0  4995.5    .045       0
  5395.5     .16       0  5499.9     .07       0
Bank Sta=4976.3,4995.5
XS Rating Curve= 0 ,0
Exp/Cntr=0.3,0.1

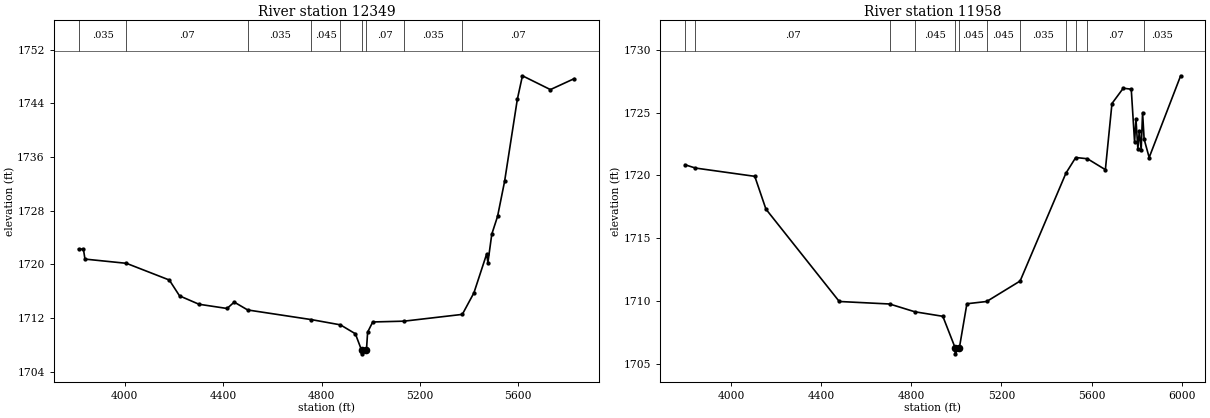
Type RM Length L Ch R = 1 ,12349   ,391,391,391
BEGIN DESCRIPTION:
Indian Creek 12349.26
END DESCRIPTION:
XS GIS Cut Line= 3
       1561705.1       6857954.5      1562436.81      6856992.65
      1562654.89       6856215.4
#Sta/Elev= 30
  3811.9  1722.3  3831.4 1722.25  3837.7 1720.78  4006.3 1720.15  4180.8 1717.66
  4222.4  1715.3  4301.4 1714.05  4415.7 1713.42  4444.8 1714.37  4499.5  1713.2
  4758.8 1711.76  4876.9 1710.98  4937.6 1709.65  4963.3 1707.16  4963.8 1706.66
  4982.6 1707.16  4987.5 1709.89  5008.3 1711.41  5135.8 1711.53  5372.7 1712.54
  5419.9 1715.75  5471.6 1721.53  5476.8 1720.26  5492.6  1724.5    5516 1727.14
  5544.6 1732.35  5596.5  1744.6  5617.3  1748.1    5731 1746.04  5827.7 1747.67
#Mann= 9 ,-1 , 0
  3811.9    .035       0  4006.3     .07       0  4499.5    .035       0
  4758.8    .045       0  4876.9     .07       0  4963.3     .07       0
  4982.6     .07       0  5135.8    .035       0  5372.7     .07       0
Bank Sta=4963.3,4982.6
XS Rating Curve= 0 ,0
Exp/Cntr=0.3,0.1

Type RM Length L Ch R = 1 ,11958   ,579,579,579
BEGIN DESCRIPTION:
Indian Creek 11958.14
END DESCRIPTION:
XS GIS Cut Line= 3
      1561858.61      6858068.69      1562740.63      6857227.02
      1563320.23      6856437.24
#Sta/Elev= 30
  3796.7 1720.85  3842.6 1720.59  4105.9 1719.93  4155.3 1717.32  4480.8 1709.96
  4704.4 1709.76  4816.1 1709.14  4940.3 1708.78  4994.5 1706.29    4995 1705.79
  5013.9 1706.29  5047.1 1709.78  5134.9 1709.96  5283.2 1711.59  5486.5 1720.18
    5530 1721.43    5582 1721.33  5661.5 1720.46  5690.8 1725.73  5740.9 1726.95
  5776.4 1726.87  5791.1 1722.67  5797.3 1724.47  5805.7 1722.11  5811.9 1723.52
  5820.4 1722.04  5826.6 1725.01  5833.5 1722.89  5855.9 1721.43  5995.5 1727.94
#Mann= 12 ,-1 , 0
  3796.7    .035       0  3842.6     .07       0  4704.4    .035       0
  4816.1    .045       0  4994.5    .045       0  5013.9    .045       0
  5134.9    .045       0  5283.2    .035       0  5486.5    .045       0
    5530    .035       0    5582     .07       0  5833.5    .035       0
Bank Sta=4994.5,5013.9
XS Rating Curve= 0 ,0
Exp/Cntr=0.3,0.1