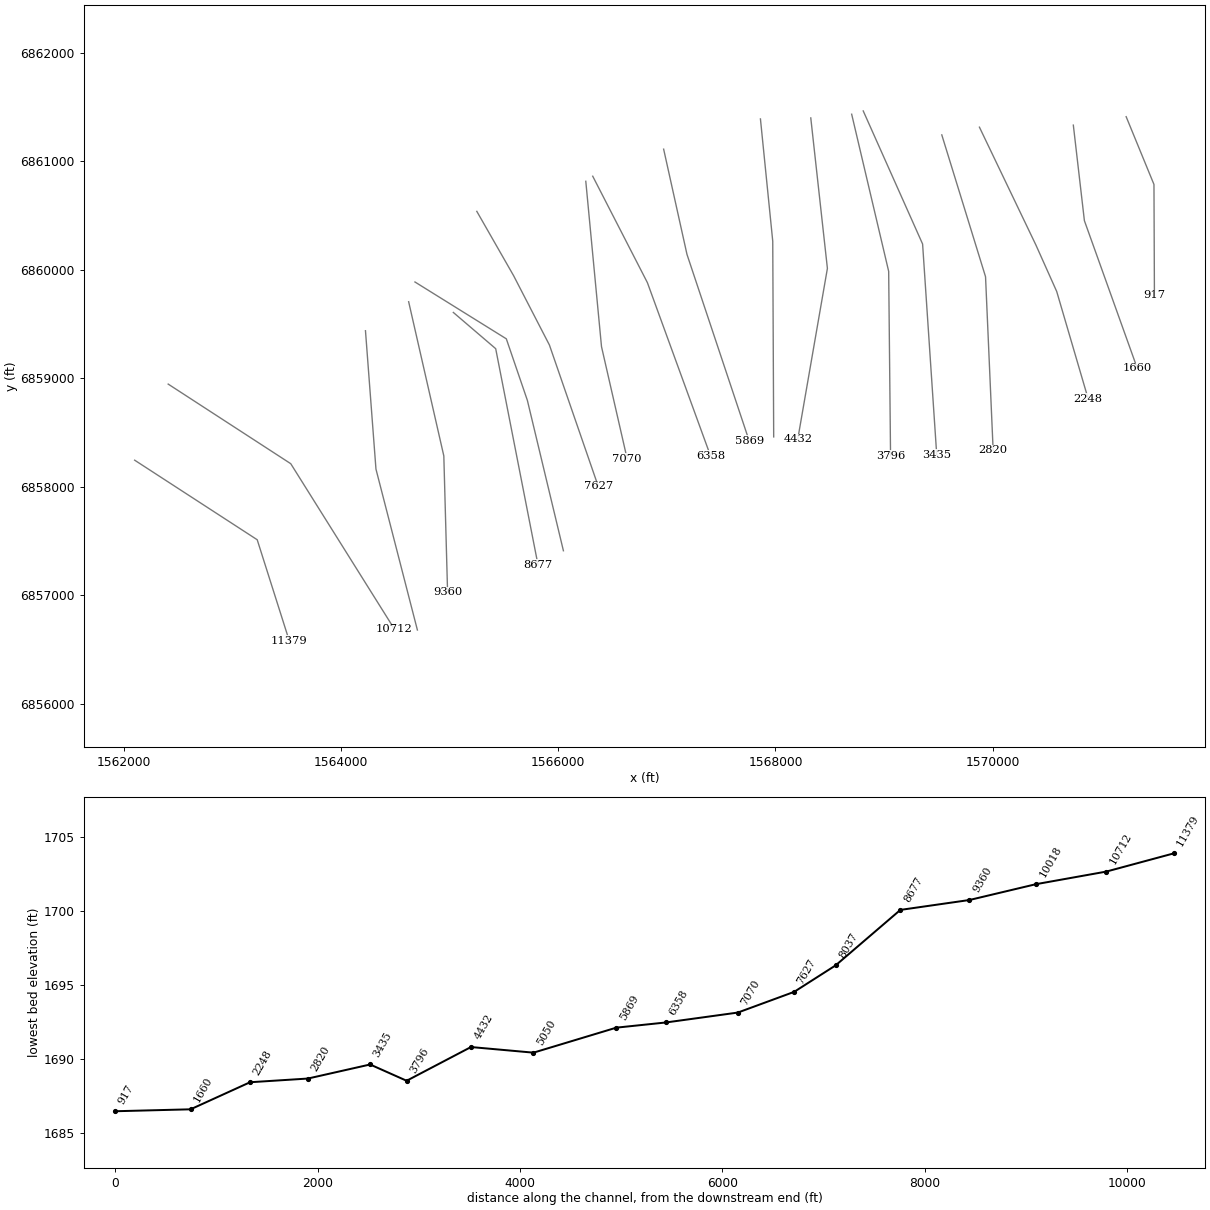
HEC-RAS study Indian Creek.prj: Indian Creek Base Level Engineering

--- Indian Creek.g01 (geometry) --- (continued)

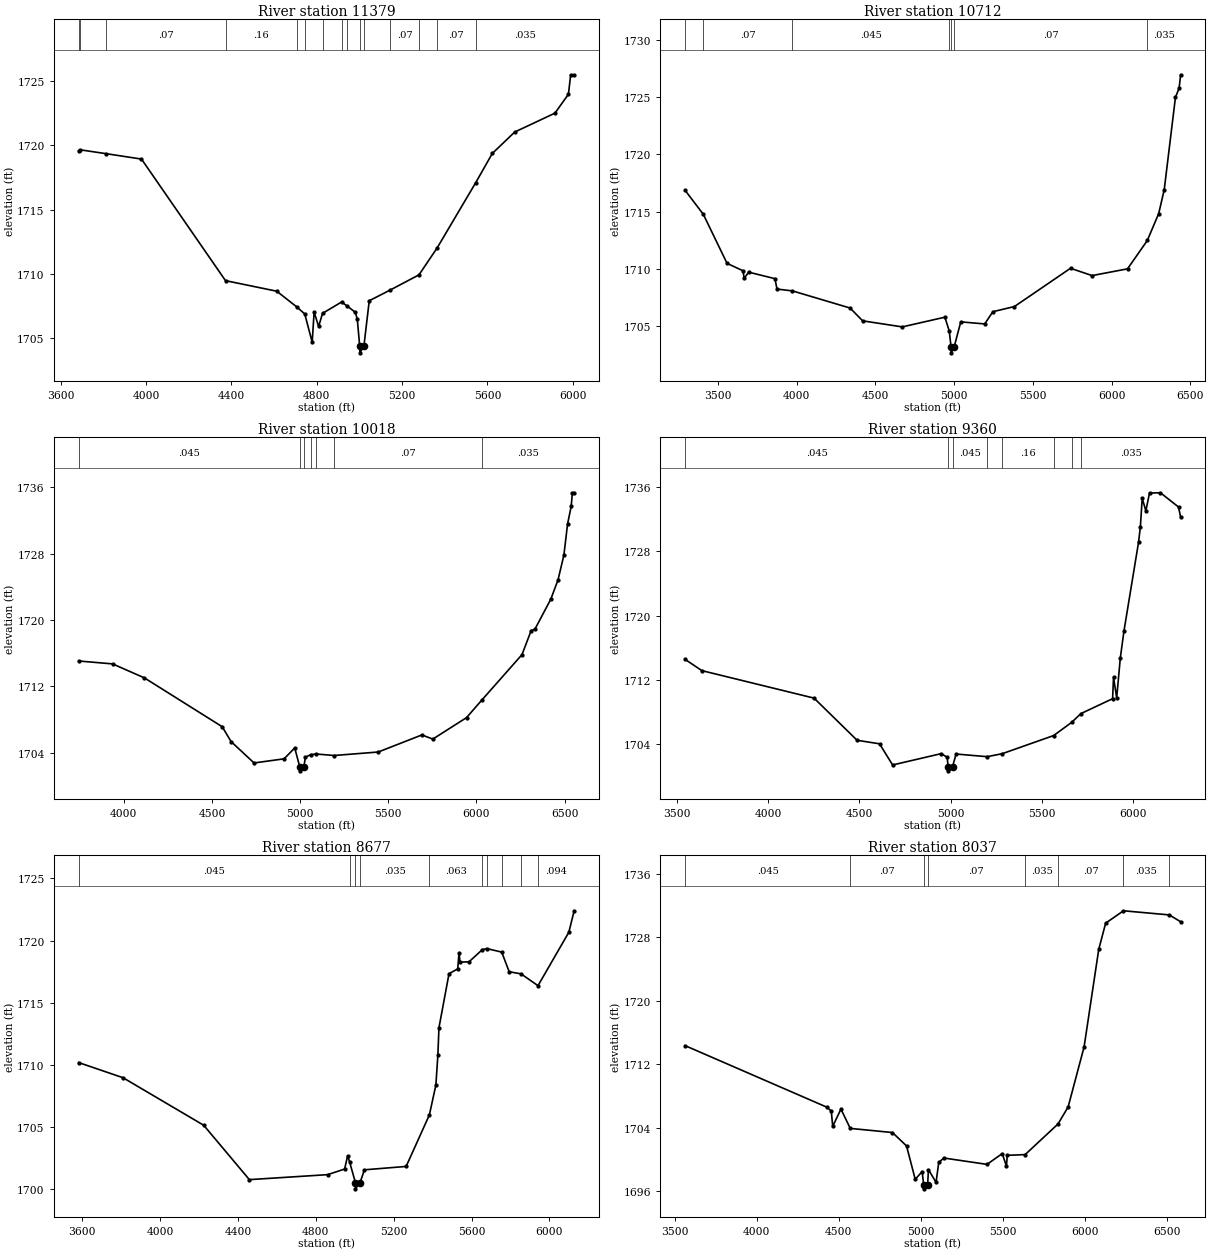
Type RM Length L Ch R = 1 ,11379   ,667,667,667
BEGIN DESCRIPTION:
Indian Creek 11379.4
END DESCRIPTION:
XS GIS Cut Line= 3
      1562097.98      6858246.86      1563226.74      6857513.48
      1563521.98      6856582.35
#Sta/Elev= 30
  3683.8 1719.56  3690.6 1719.65  3812.1 1719.35  3978.4 1718.93  4372.3 1709.48
  4612.5 1708.66    4707 1707.43  4743.8 1706.89  4778.6  1704.7  4787.7 1707.04
  4808.8 1705.92  4827.2 1706.94  4916.3 1707.82  4940.8 1707.53  4980.9 1707.02
  4990.1 1706.48  5001.5 1704.37    5002 1703.87  5020.9 1704.37  5046.1 1707.92
    5143 1708.74  5279.2 1709.93  5364.6 1712.03    5545 1717.09  5623.1 1719.37
    5728 1721.03  5916.8  1722.5  5979.8 1723.97  5990.3 1725.48  6006.7 1725.44
#Mann= 15 ,-1 , 0
  3683.8     .07       0  3690.6    .035       0  3812.1     .07       0
  4372.3     .16       0    4707    .035       0  4743.8     .07       0
  4827.2    .035       0  4916.3    .045       0  4940.8    .035       0
  5001.5    .035       0  5020.9    .035       0    5143     .07       0
  5279.2    .035       0  5364.6     .07       0    5545    .035       0
Bank Sta=5001.5,5020.9
XS Rating Curve= 0 ,0
Exp/Cntr=0.3,0.1

Type RM Length L Ch R = 1 ,10712   ,694,694,694
BEGIN DESCRIPTION:
Indian Creek 10719.42
END DESCRIPTION:
XS GIS Cut Line= 3
      1562406.83      6858948.17      1563535.69      6858214.49
       1564490.5      6856689.81
#Sta/Elev= 30
  3292.5 1716.86  3408.2 1714.76  3558.8 1710.47    3660 1709.82  3667.5 1709.16
  3695.8  1709.7  3862.8 1709.13  3875.8 1708.22  3973.9 1708.06  4339.8 1706.56
  4419.4 1705.44  4670.9 1704.91  4941.5 1705.76  4969.3 1704.54  4980.6 1703.14
  4981.1 1702.64    5000 1703.14  5042.2 1705.35  5194.2 1705.17  5246.1 1706.24
  5382.8 1706.69  5738.8 1710.04  5875.6  1709.4  6100.7 1709.99  6226.2 1712.47
  6298.4 1714.82  6333.7 1716.92  6404.8 1724.99  6428.1  1725.8  6437.8 1726.97
#Mann= 7 ,-1 , 0
  3292.5    .035       0  3408.2     .07       0  3973.9    .045       0
  4969.3     .07       0  4980.6     .07       0    5000     .07       0
  6226.2    .035       0
Bank Sta=4980.6,5000
XS Rating Curve= 0 ,0
Exp/Cntr=0.3,0.1

Type RM Length L Ch R = 1 ,10018   ,658,658,658
BEGIN DESCRIPTION:
Indian Creek 10017.77
END DESCRIPTION:
XS GIS Cut Line= 3
      1564223.86      6859440.09      1564320.49      6858164.52
      1564702.07      6856681.55
#Sta/Elev= 30
  3744.2 1715.04  3936.8 1714.69  4117.4    1713  4558.6 1707.11  4608.8 1705.32
  4739.1 1702.74  4909.6 1703.24  4969.8 1704.55  4998.1 1702.29  4998.6 1701.79
  5021.8 1702.29  5030.2 1703.43    5060 1703.74  5092.4 1703.82  5192.8 1703.64
  5443.2 1704.06    5691 1706.12    5753 1705.62  5944.2 1708.21  6029.5 1710.29
  6258.9 1715.81  6310.7 1718.71  6331.2 1718.84  6422.5 1722.51  6463.2 1724.83
  6496.4 1727.81  6517.1 1731.55  6537.7 1733.69  6544.6 1735.33  6554.7 1735.26
#Mann= 7 ,-1 , 0
  3744.2    .045       0  4998.1    .045       0  5021.8    .045       0
    5060     .07       0  5092.4    .045       0  5192.8     .07       0
  6029.5    .035       0
Bank Sta=4998.1,5021.8
XS Rating Curve= 0 ,0
Exp/Cntr=0.3,0.1

Type RM Length L Ch R = 1 ,9360    ,683,683,683
BEGIN DESCRIPTION:
Indian Creek 9360.15
END DESCRIPTION:
XS GIS Cut Line= 3
      1564621.56      6859707.37      1564945.49      6858286.05
      1564980.21      6857027.39
#Sta/Elev= 30
  3544.4 1714.58  3636.1 1713.18  4251.4 1709.76  4487.4 1704.52  4610.4 1704.08
  4682.2 1701.45  4948.9 1702.86  4981.1 1702.41  4986.7 1701.22  4987.2 1700.72
  5010.5 1701.22  5030.2 1702.81  5200.5 1702.48  5282.9 1702.85  5565.4 1705.11
  5663.3 1706.74  5714.9 1707.84  5888.3 1709.69  5893.3 1712.37  5910.6 1709.78
  5930.6 1714.76  5950.6 1718.11  6030.6 1729.14  6040.6 1731.08  6050.6 1734.61
  6070.6 1733.04  6090.6 1735.26  6150.7 1735.29  6249.6 1733.52  6261.3 1732.27
#Mann= 8 ,-1 , 0
  3544.4    .045       0  4986.7    .045       0  5010.5    .045       0
  5200.5     .07       0  5282.9     .16       0  5565.4    .035       0
  5663.3    .094       0  5714.9    .035       0
Bank Sta=4986.7,5010.5
XS Rating Curve= 0 ,0
Exp/Cntr=0.3,0.1

Type RM Length L Ch R = 1 ,8677    ,640,640,640
BEGIN DESCRIPTION:
Indian Creek 8729.752
END DESCRIPTION:
XS GIS Cut Line= 3
      1565033.23      6859608.51      1565423.26      6859274.62
      1565813.17      6857281.01
#Sta/Elev= 30
  3582.4  1710.2  3810.6 1708.98  4224.8 1705.16  4459.2 1700.79    4861 1701.19
  4948.3 1701.64    4964 1702.71  4973.6 1702.24  5003.7 1700.55  5004.2 1700.05
  5027.5 1700.55  5050.2 1701.58  5264.2 1701.85  5383.6 1705.99    5417 1708.39
  5427.2 1710.78  5432.8    1713  5484.4 1717.34  5529.1 1717.73  5535.9 1719.03
    5541 1718.27  5587.4  1718.3  5655.7 1719.28  5678.5 1719.36    5755 1719.08
  5793.5  1717.5  5854.2 1717.33  5941.4 1716.38  6099.7 1720.67  6127.2  1722.4
#Mann= 10 ,-1 , 0
  3582.4    .045       0  4973.6    .035       0  5003.7    .035       0
  5027.5    .035       0  5383.6    .063       0  5655.7    .094       0
  5678.5    .125       0    5755    .094       0  5854.2    .063       0
  5941.4    .094       0
Bank Sta=5003.7,5027.5
XS Rating Curve= 0 ,0
Exp/Cntr=0.3,0.1

Type RM Length L Ch R = 1 ,8037    ,410,410,410
BEGIN DESCRIPTION:
Indian Creek 7916.965
END DESCRIPTION:
XS GIS Cut Line= 4
      1564679.72      6859889.32      1565521.08      6859365.53
      1565715.08      6858797.98      1566046.95      6857412.03
#Sta/Elev= 30
  3564.5 1714.33  4426.3 1706.59  4454.2  1706.1  4462.9 1704.17  4513.1 1706.34
  4569.7 1703.91  4826.5 1703.39  4912.3  1701.7  4965.1  1697.5  5007.4 1698.48
  5016.4  1696.8  5016.9  1696.3  5040.6  1696.8  5045.6 1698.72  5091.9 1697.11
  5108.3 1699.63  5139.6 1700.18  5402.1 1699.38  5494.7 1700.74  5520.2 1699.16
  5525.5 1700.52    5634 1700.61  5833.9 1704.46  5895.7 1706.61  5992.9 1714.17
  6082.1 1726.46  6124.1 1729.75  6232.6 1731.31  6511.3 1730.79  6580.5 1729.93
#Mann= 8 ,-1 , 0
  3564.5    .045       0  4569.7     .07       0  5016.4     .07       0
  5040.6     .07       0    5634    .035       0  5833.9     .07       0
  6232.6    .035       0  6511.3     .07       0
Bank Sta=5016.4,5040.6
XS Rating Curve= 0 ,0
Exp/Cntr=0.3,0.1

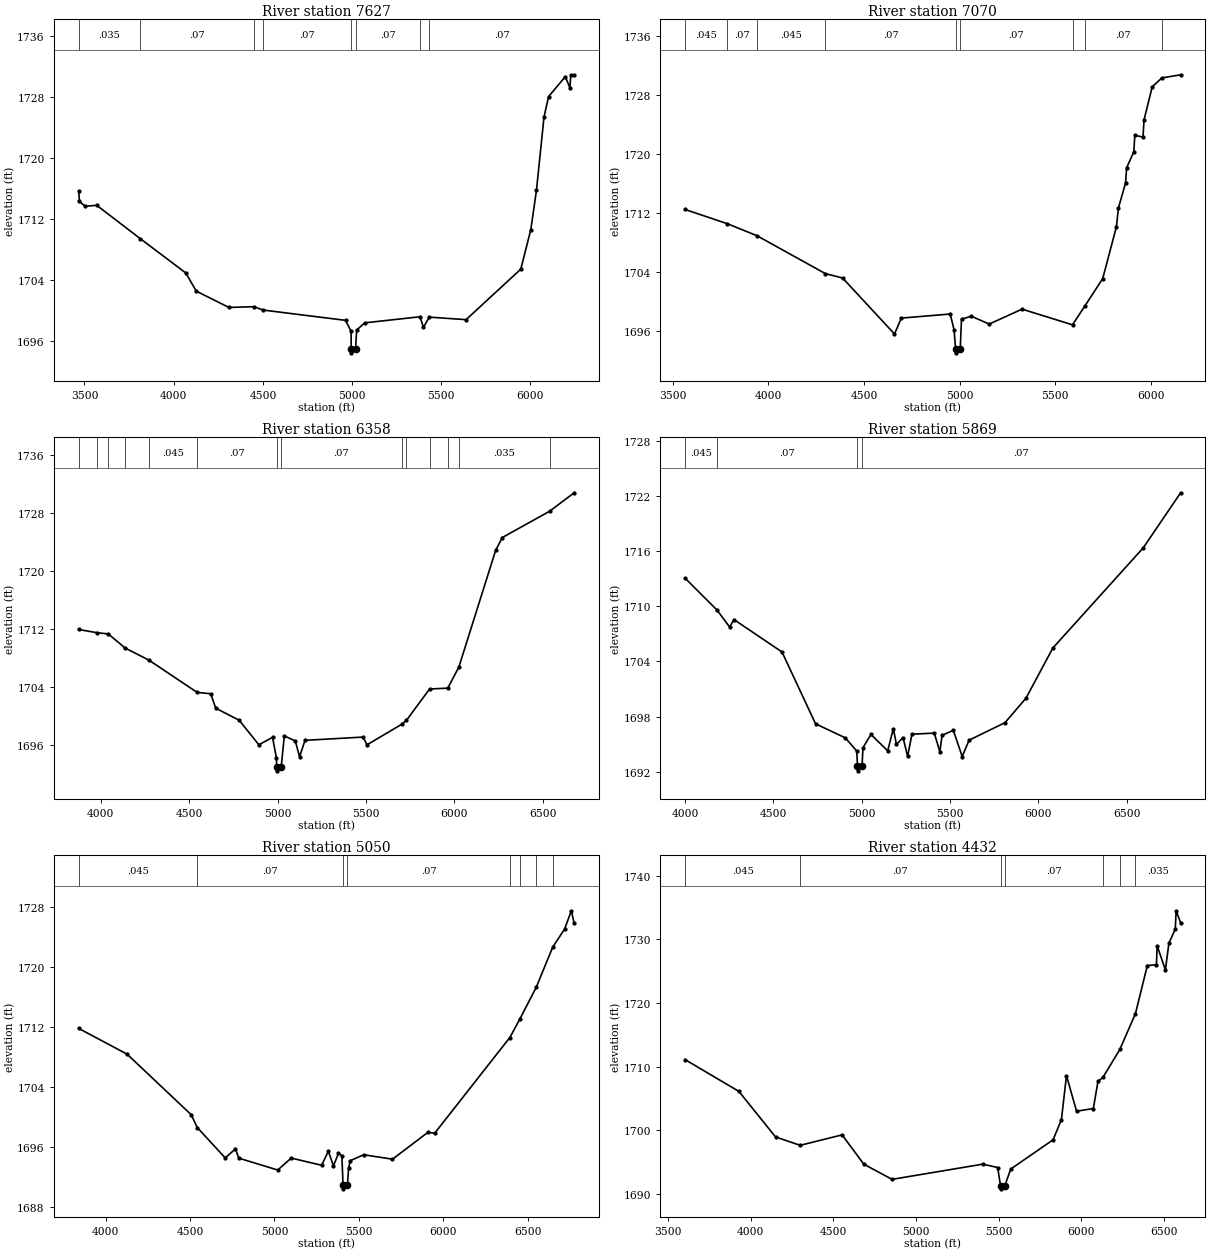
Type RM Length L Ch R = 1 ,7627    ,557,557,557
BEGIN DESCRIPTION:
Indian Creek 2.0
END DESCRIPTION:
XS GIS Cut Line= 4
      1565249.36       6860540.3      1565587.83      6859948.21
      1565918.28      6859307.95        1566367.      6858008.14
#Sta/Elev= 30
  3467.2 1715.75    3472 1714.36  3503.7 1713.72  3568.5 1713.85  3812.1 1709.49
    4068 1704.98  4126.4  1702.6  4309.6 1700.46  4450.2 1700.56  4501.3 1700.12
  4963.2 1698.77  4994.4 1697.34  4995.1 1695.01  4995.6 1694.51  5019.3 1695.01
  5025.6  1697.5  5070.7 1698.44  5380.9 1699.24  5399.9 1697.84  5432.5 1699.19
  5638.9 1698.86  5945.5 1705.48  6001.6 1710.64  6033.4 1715.81  6075.7 1725.42
  6101.4  1728.1    6195 1730.72  6220.9 1729.26  6226.2 1730.96  6244.8 1730.94
#Mann= 8 ,-1 , 0
  3467.2    .035       0  3812.1     .07       0  4450.2    .045       0
  4501.3     .07       0  4995.1     .07       0  5019.3     .07       0
  5380.9    .035       0  5432.5     .07       0
Bank Sta=4995.1,5019.3
XS Rating Curve= 0 ,0
Exp/Cntr=0.3,0.1

Type RM Length L Ch R = 1 ,7070    ,712,712,712
BEGIN DESCRIPTION:
Indian Creek 6894.872
END DESCRIPTION:
XS GIS Cut Line= 3
      1566253.13       6860817.4      1566397.84      6859293.22
      1566633.74      6858261.17
#Sta/Elev= 30
  3565.2  1712.5  3785.4 1710.58  3940.2 1708.96    4298 1703.83  4388.3 1703.23
  4659.5 1695.66  4695.3 1697.81  4950.8 1698.36  4970.9 1696.21  4978.9 1693.61
  4979.4 1693.11  5003.1 1693.61  5009.7 1697.67  5061.3 1698.06  5154.4    1697
  5326.2 1699.02  5589.8  1696.9    5653 1699.39  5747.8 1703.16  5819.3 1710.17
  5829.9 1712.72  5867.3 1716.11  5872.5 1718.13  5910.3 1720.31  5915.4 1722.53
  5958.4  1722.3  5963.5 1724.61  6006.5  1729.1  6056.5 1730.29  6154.9 1730.72
#Mann= 9 ,-1 , 0
  3565.2    .045       0  3785.4     .07       0  3940.2    .045       0
    4298     .07       0  4978.9     .07       0  5003.1     .07       0
  5589.8    .035       0    5653     .07       0  6056.5    .035       0
Bank Sta=4978.9,5003.1
XS Rating Curve= 0 ,0
Exp/Cntr=0.3,0.1

Type RM Length L Ch R = 1 ,6358    ,489,489,489
BEGIN DESCRIPTION:
Indian Creek 6357.98
END DESCRIPTION:
XS GIS Cut Line= 3
        1566317.      6860864.21      1566820.49      6859883.27
      1567402.08      6858286.07
#Sta/Elev= 30
  3874.4 1711.95  3980.1  1711.5  4041.7 1711.34  4138.1 1709.38  4271.2 1707.73
  4544.4 1703.27  4621.6 1703.08  4649.4 1701.09  4782.5 1699.42  4893.5 1696.04
    4971 1697.06  4993.3 1694.18  4994.2 1692.94  4994.7 1692.44  5019.8 1692.94
  5037.6 1697.26  5099.7 1696.57    5124 1694.38  5154.6 1696.65  5482.8  1697.1
  5505.5 1696.04  5701.1 1698.86  5728.3 1699.41  5858.9 1703.73  5962.1 1703.86
  6024.8 1706.77  6232.7 1722.87  6270.3 1724.64  6537.8 1728.27  6676.8 1730.82
#Mann= 14 ,-1 , 0
  3874.4    .045       0  3980.1     .07       0  4041.7    .045       0
  4138.1     .07       0  4271.2    .045       0  4544.4     .07       0
  4994.2     .07       0  5019.8     .07       0  5701.1    .035       0
  5728.3     .07       0  5858.9    .035       0  5962.1     .07       0
  6024.8    .035       0  6537.8     .07       0
Bank Sta=4994.2,5019.8
XS Rating Curve= 0 ,0
Exp/Cntr=0.3,0.1

Type RM Length L Ch R = 1 ,5869    ,819,819,819
BEGIN DESCRIPTION:
Indian Creek 5869.23
END DESCRIPTION:
XS GIS Cut Line= 3
      1566970.13      6861113.69      1567185.07      6860143.69
      1567758.01      6858424.89
#Sta/Elev= 30
  4000.9 1713.07    4182 1709.59  4252.6 1707.76  4277.9 1708.56  4549.6 1705.03
  4739.5 1697.21  4908.1 1695.68  4972.8 1694.24  4976.8 1692.59  4977.3 1692.09
  5002.5 1692.59  5007.9 1694.61  5053.1 1696.05    5148 1694.27  5179.6 1696.68
  5197.6 1694.96  5234.5 1695.72  5260.8 1693.67    5285 1696.08  5411.5  1696.2
  5443.1 1694.18  5455.8 1695.95  5519.1 1696.51  5569.6 1693.65  5608.7 1695.43
  5812.1 1697.34  5930.2 1699.99    6083 1705.47  6594.3 1716.37  6806.2 1722.37
#Mann= 4 ,-1 , 0
  4000.9    .045       0    4182     .07       0  4976.8     .07       0
  5002.5     .07       0
Bank Sta=4976.8,5002.5
XS Rating Curve= 0 ,0
Exp/Cntr=0.3,0.1

Type RM Length L Ch R = 1 ,5050    ,618,618,618
BEGIN DESCRIPTION:
Indian Creek 5049.9
END DESCRIPTION:
XS GIS Cut Line= 3
      1567861.63      6861392.32        1567975.      6860265.22
      1567983.68      6858461.33
#Sta/Elev= 30
  3839.4 1711.83  4126.5 1708.39  4507.1 1700.29  4542.4 1698.59  4708.1 1694.53
  4768.4 1695.73  4788.5  1694.5  5019.4 1692.91  5099.4 1694.51  5279.4 1693.55
  5319.4 1695.42  5349.4 1693.46  5379.4 1695.15  5399.4 1694.82  5406.4  1690.9
  5406.9  1690.4  5432.5  1690.9  5439.4 1693.16  5449.4 1694.17  5529.4 1694.95
  5699.4 1694.36  5909.4 1697.95  5949.4 1697.83  6394.9 1710.61  6453.2 1713.04
  6551.1 1717.31    6649 1722.69  6719.4  1725.1  6759.4 1727.54  6776.1 1725.88
#Mann= 8 ,-1 , 0
  3839.4    .045       0  4542.4     .07       0  5406.4     .07       0
  5432.5     .07       0  6394.9    .035       0  6453.2     .07       0
  6551.1    .035       0    6649     .07       0
Bank Sta=5406.4,5432.5
XS Rating Curve= 0 ,0
Exp/Cntr=0.3,0.1

Type RM Length L Ch R = 1 ,4432    ,636,636,636
BEGIN DESCRIPTION:
Indian Creek 4432.251
END DESCRIPTION:
XS GIS Cut Line= 3
      1568325.28      6861401.58      1568478.43      6860014.61
      1568205.01      6858438.04
#Sta/Elev= 30
  3604.6 1711.09  3930.1 1706.09  4151.5 1698.93  4300.4 1697.62  4553.8 1699.26
  4684.7 1694.66  4855.7 1692.27    5404 1694.66  5493.9 1694.13  5511.3 1691.28
  5511.8 1690.78  5537.4 1691.28    5573 1693.89  5828.8 1698.48  5879.5 1701.66
    5910 1708.57  5970.9 1702.98  6072.4  1703.4  6100.2 1707.65    6132 1708.36
  6232.6 1712.69    6327 1718.32  6398.8 1725.88  6453.4 1725.99  6458.5 1728.95
    6508 1725.19  6529.1 1729.37  6567.8 1731.61  6572.8 1734.48  6600.1 1732.58
#Mann= 7 ,-1 , 0
  3604.6    .045       0  4300.4     .07       0  5511.3     .07       0
  5537.4     .07       0    6132    .035       0  6232.6     .07       0
    6327    .035       0
Bank Sta=5511.3,5537.4
XS Rating Curve= 0 ,0
Exp/Cntr=0.3,0.1

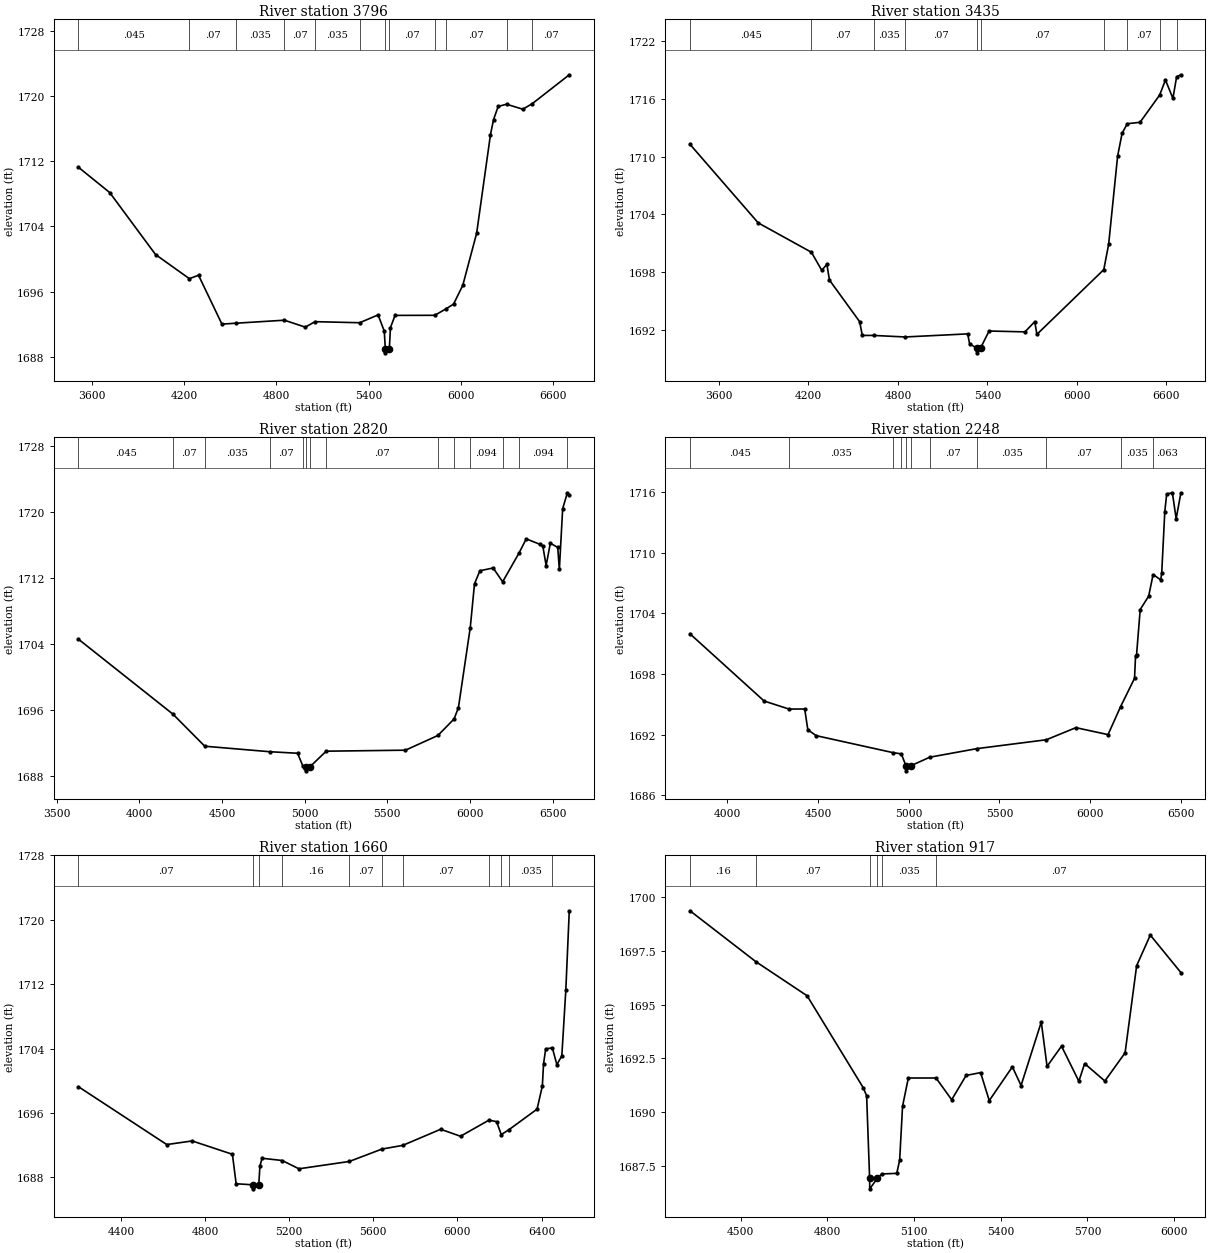
Type RM Length L Ch R = 1 ,3796    ,361,361,361
BEGIN DESCRIPTION:
Indian Creek 3795.88
END DESCRIPTION:
XS GIS Cut Line= 3
      1568701.93      6861435.77      1569042.71      6859987.44
      1569060.07      6858286.01
#Sta/Elev= 30
  3513.7 1711.25  3716.9 1708.15  4014.8 1700.55  4234.7 1697.59  4294.2 1698.01
  4446.3 1692.02  4536.1 1692.13  4852.2  1692.5  4987.7 1691.65  5051.4 1692.32
  5341.2 1692.19    5461 1693.15    5501 1691.16  5507.9    1689  5508.4  1688.5
  5534.1    1689  5541.1 1691.59  5571.1 1693.09    5829  1693.1  5901.1 1693.88
  5951.1 1694.47  6011.1 1696.77  6101.1 1703.15  6191.1 1715.25  6211.1 1717.09
  6241.1  1718.7  6295.3 1718.97  6401.1 1718.36  6462.7 1719.04  6703.1 1722.58
#Mann= 12 ,-1 , 0
  3513.7    .045       0  4234.7     .07       0  4536.1    .035       0
  4852.2     .07       0  5051.4    .035       0  5341.2     .07       0
  5507.9     .07       0  5534.1     .07       0    5829    .035       0
  5901.1     .07       0  6295.3    .035       0  6462.7     .07       0
Bank Sta=5507.9,5534.1
XS Rating Curve= 0 ,0
Exp/Cntr=0.3,0.1

Type RM Length L Ch R = 1 ,3435    ,615,615,615
BEGIN DESCRIPTION:
Indian Creek 3434.83
END DESCRIPTION:
XS GIS Cut Line= 3
      1568808.44      6861465.91      1569355.21      6860239.18
      1569485.42       6858294.7
#Sta/Elev= 30
  3405.3 1711.28  3862.8 1703.11  4219.5 1700.06  4288.9 1698.18  4323.1  1698.8
  4340.8 1697.16  4543.1 1692.84  4560.8 1691.41    4636 1691.41  4847.7 1691.25
  5267.4 1691.57  5280.7 1690.53  5327.8  1690.1  5328.3  1689.6    5354  1690.1
    5411 1691.87  5651.6 1691.78  5717.4 1692.84  5731.7 1691.52  6180.2 1698.25
  6212.8 1700.88  6272.9 1710.04    6303 1712.43  6337.9 1713.42  6423.3 1713.57
  6554.9  1716.4  6593.7 1717.97  6643.8 1716.06  6668.7  1718.3  6697.2 1718.51
#Mann= 10 ,-1 , 0
  3405.3    .045       0  4219.5     .07       0    4636    .035       0
  4847.7     .07       0  5327.8     .07       0    5354     .07       0
  6180.2    .035       0  6337.9     .07       0  6554.9    .063       0
  6668.7    .094       0
Bank Sta=5327.8,5354
XS Rating Curve= 0 ,0
Exp/Cntr=0.3,0.1

Type RM Length L Ch R = 1 ,2820    ,572,572,572
BEGIN DESCRIPTION:
Indian Creek 2819.537
END DESCRIPTION:
XS GIS Cut Line= 3
      1569532.03      6861245.12       1569934.9      6859937.79
        1570005.      6858338.02
#Sta/Elev= 30
    3632 1704.59  4204.1 1695.51  4396.4 1691.63  4791.9 1690.96  4957.9 1690.78
  4988.4 1689.29  5006.6 1689.15  5007.1 1688.65  5033.1 1689.15  5130.8 1691.03
  5610.4 1691.15  5806.5 1692.93  5904.4 1694.93  5930.7  1696.3  6002.3 1705.99
    6028 1711.29  6060.8 1712.87  6140.9 1713.21  6198.1 1711.53    6296 1714.97
  6341.1 1716.73  6421.2 1716.09  6441.2 1715.86  6461.2  1713.5  6486.7  1716.2
  6531.3  1715.7  6541.3 1713.03  6561.3 1720.39  6589.7 1722.31  6601.3 1722.06
#Mann= 14 ,-1 , 0
    3632    .045       0  4204.1     .07       0  4396.4    .035       0
  4791.9     .07       0  4988.4     .16       0  5006.6     .07       0
  5033.1     .16       0  5130.8     .07       0  5806.5     .16       0
  5904.4    .035       0  6002.3    .094       0  6198.1    .035       0
    6296    .094       0  6589.7    .035       0
Bank Sta=5006.6,5033.1
XS Rating Curve= 0 ,0
Exp/Cntr=0.3,0.1

Type RM Length L Ch R = 1 ,2248    ,588,588,588
BEGIN DESCRIPTION:
Indian Creek 2248.496
END DESCRIPTION:
XS GIS Cut Line= 4
      1569878.65      6861316.28      1570398.95      6860229.84
      1570590.46      6859801.68      1570879.99      6858813.04
#Sta/Elev= 30
  3795.4 1701.98  4203.7 1695.32  4341.1 1694.52  4427.3 1694.53  4444.4 1692.48
  4489.8 1691.89    4912 1690.21  4959.5 1690.08  4984.9  1688.9  4985.4  1688.4
  5011.5  1688.9  5115.8 1689.75  5375.2  1690.6  5758.2 1691.48  5920.9 1692.68
  6098.1 1691.99  6167.1 1694.76    6244 1697.57  6249.7 1699.83  6254.9 1699.85
  6275.2 1704.39  6321.7 1705.71  6346.3 1707.86  6388.6 1707.32  6393.8 1708.05
  6410.7  1714.1  6421.1 1715.84  6452.4 1715.96  6473.2 1713.39  6499.2 1715.94
#Mann= 11 ,-1 , 0
  3795.4    .045       0  4341.1    .035       0    4912     .07       0
  4959.5     .16       0  4984.9     .07       0  5011.5     .16       0
  5115.8     .07       0  5375.2    .035       0  5758.2     .07       0
  6167.1    .035       0  6346.3    .063       0
Bank Sta=4984.9,5011.5
XS Rating Curve= 0 ,0
Exp/Cntr=0.3,0.1

Type RM Length L Ch R = 1 ,1660    ,743,743,743
BEGIN DESCRIPTION:
Indian Creek 1.0
END DESCRIPTION:
XS GIS Cut Line= 3
      1570743.48      6861335.18      1570845.44      6860454.32
      1571332.91      6859092.48
#Sta/Elev= 30
  4198.3 1699.26  4618.3 1692.07  4739.1 1692.52  4930.3 1690.86  4948.1  1687.2
  5028.3 1687.07  5028.8 1686.57  5055.5 1687.07  5061.2 1689.41  5071.3 1690.37
  5166.9 1690.09  5246.4 1689.06  5485.8 1689.97  5641.1 1691.51    5740 1691.97
  5920.2 1693.97  6014.5  1693.1  6149.4  1695.1  6185.8 1694.92  6208.3 1693.31
    6245 1693.92  6378.4 1696.47  6403.5 1699.35  6409.1 1702.07  6419.4 1703.96
    6451 1704.08  6472.5    1702  6496.1 1703.09    6515 1711.24  6531.5 1721.11
#Mann= 11 ,-1 , 0
  4198.3     .07       0  5028.3     .07       0  5055.5     .07       0
  5166.9     .16       0  5485.8     .07       0  5641.1    .035       0
    5740     .07       0  6149.4    .035       0  6208.3     .07       0
    6245    .035       0    6451    .063       0
Bank Sta=5028.3,5055.5
XS Rating Curve= 0 ,0
Exp/Cntr=0.3,0.1

Type RM Length L Ch R = 1 ,917     ,0,0,0
BEGIN DESCRIPTION:
Indian Creek 916.553
END DESCRIPTION:
XS GIS Cut Line= 3
        1571230.        6861413.      1571486.18      6860788.18
      1571490.43      6859764.99
#Sta/Elev= 30
  4324.7 1699.36  4552.1    1697    4730 1695.41  4924.5 1691.13  4935.9 1690.76
  4946.2 1686.94  4946.7 1686.44  4973.5 1686.94  4988.1 1687.13  5040.2 1687.16
  5050.2 1687.78  5060.2 1690.28  5080.2 1691.59    5176 1691.59  5230.2 1690.58
  5280.2 1691.71  5330.2 1691.84  5360.2 1690.54  5440.2 1692.11  5470.2 1691.24
  5540.2 1694.19  5560.2 1692.13  5610.2 1693.07  5670.2 1691.44  5690.2 1692.26
  5760.2 1691.45  5830.2 1692.76  5870.2 1696.81  5917.4 1698.23  6023.2 1696.49
#Mann= 6 ,-1 , 0
  4324.7     .16       0  4552.1     .07       0  4946.2    .035       0
  4973.5     .07       0  4988.1    .035       0    5176     .07       0
Bank Sta=4946.2,4973.5
XS Rating Curve= 0 ,0
Exp/Cntr=0.3,0.1

Chan Stop Cuts=-1
Use User Specified Reach Order=0
Composite Channel Slope=5