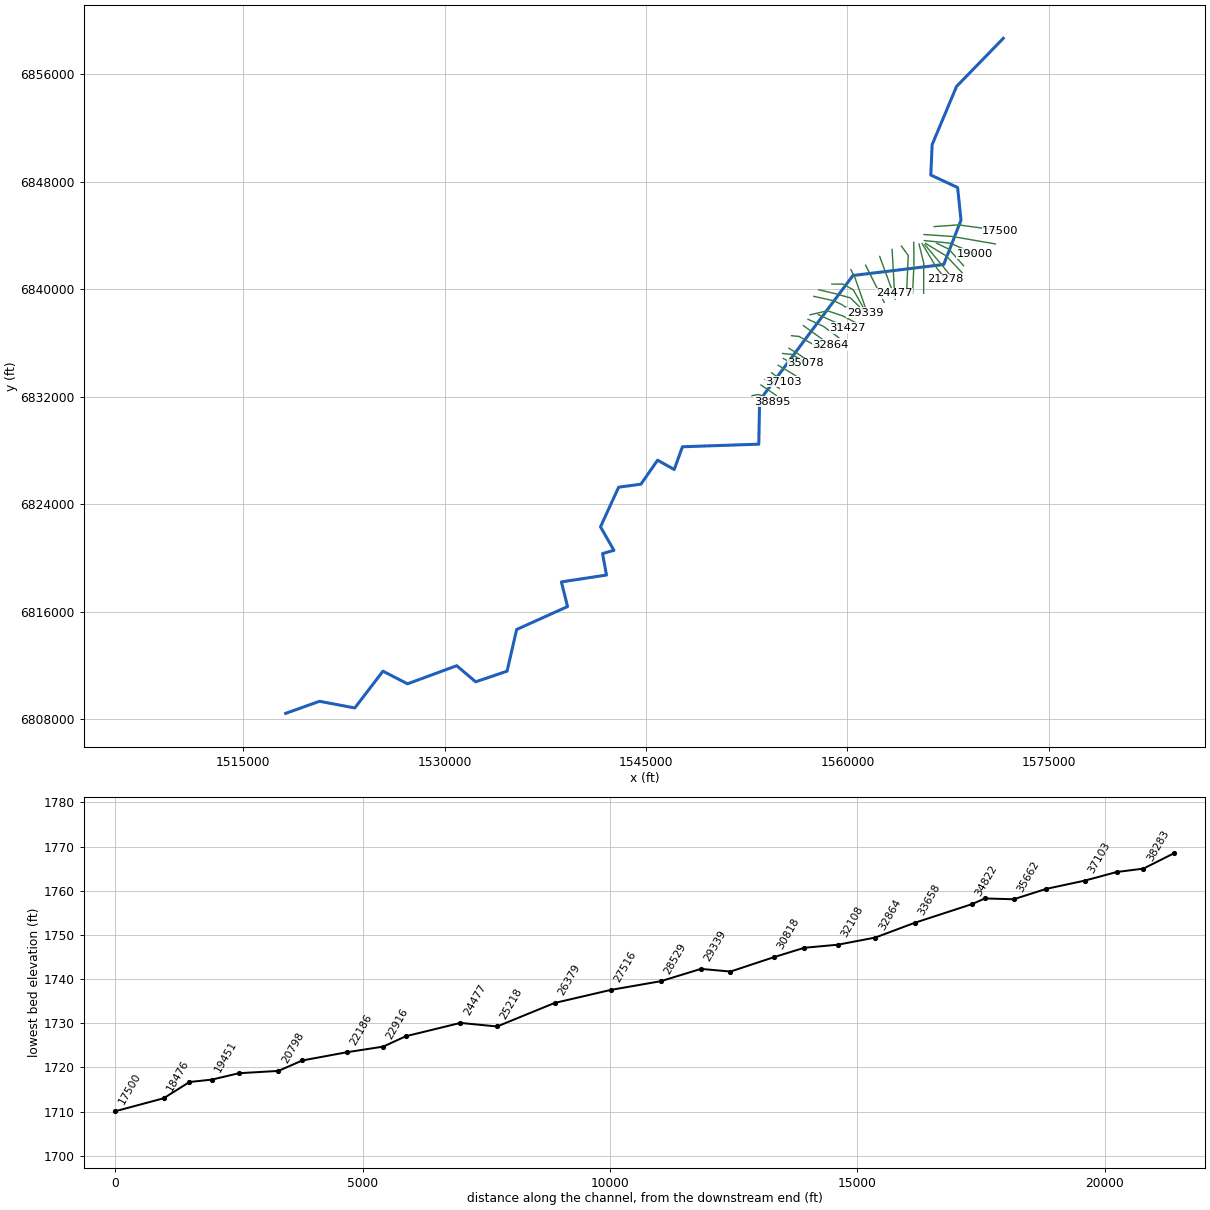
--- Little Elm Creek.prj (project) ---

Proj Title=Little Elm Creek Base Level Engineering
Current Plan=p01
Default Exp/Contr=0.3,0.1
English Units
Geom File=g01
Flow File=f01
Plan File=p01
BEGIN DESCRIPTION:
Little Elm Creek
END DESCRIPTION:

--- Little Elm Creek.p01 (plan) ---

Plan Title=Multiple Run
Short Identifier=Multiple
Geom File=g01
Flow File=f01
Subcritical Flow
K Sum by GR= 0
Std Step Tol= 0.01
Critical Tol= 0.01
Num of Std Step Trials= 20
Max Error Tol= 0.3
Flow Tol Ratio= 0.001
Split Flow NTrial= 30
Split Flow Tol= 0.02
Split Flow Ratio= 0.02
Log Output Level= 0
Friction Slope Method= 1
Unsteady Friction Slope Method= 2
Unsteady Bridges Friction Slope Method= 1
Parabolic Critical Depth
Global Vel Dist=  1 , 1 , 1
Global Log Level= 0
CheckData=True
Encroach Param= -1, 0, 0, 0
BEGIN DESCRIPTION:
Multiple Run
END DESCRIPTION:

--- Little Elm Creek.f01 (steady flow) ---

Flow Title=Multiple
Number of Profiles=7
Profile Names=10-year,25-year,50-year,1pct_min,100-year,1pct_plu,500-year
River Rch & RM= Little Elm Creek,Reach-1,38895
    2525    3784    4904    3141    6268   12506   10380
River Rch & RM= Little Elm Creek,Reach-1,27516
    2764    4147    5380    3449    6883   13733   11416
River Rch & RM= Little Elm Creek,Reach-1,26379
    2906    4362    5661    3630    7243   14452   12018
River Rch & RM= Little Elm Creek,Reach-1,18476
    2932    4397    5701    3654    7290   14545   12076
River Rch & RM= Little Elm Creek,Reach-1,12262
    2988    4481    5810    3723    7428   14822   12305
River Rch & RM= Little Elm Creek,Reach-1,8500
    3148    4727    6134    3934    7848   15660   13018
River Rch & RM= Little Elm Creek,Reach-1,2500
    3178    4769    6188    3967    7915   15792   13121
Boundary for River Rch & Prof#=Little Elm Creek,Reach-1,1
Up Type=0
Dn Type=3
Dn Slope=0.005
Boundary for River Rch & Prof#=Little Elm Creek,Reach-1,2
Up Type=0
Dn Type=3
Dn Slope=0.005
Boundary for River Rch & Prof#=Little Elm Creek,Reach-1,3
Up Type=0
Dn Type=3
Dn Slope=0.005
Boundary for River Rch & Prof#=Little Elm Creek,Reach-1,4
Up Type=0
Dn Type=3
Dn Slope=0.005
Boundary for River Rch & Prof#=Little Elm Creek,Reach-1,5
Up Type=0
Dn Type=3
Dn Slope=0.005
Boundary for River Rch & Prof#=Little Elm Creek,Reach-1,6
Up Type=0
Dn Type=3
Dn Slope=0.005
Boundary for River Rch & Prof#=Little Elm Creek,Reach-1,7
Up Type=0
Dn Type=3
Dn Slope=0.005

--- Little Elm Creek.g01 (geometry) ---

Geom Title=Existing Conditions

River Reach=Little Elm Creek,Reach-1
Reach XY= 30
      1518155.00      6808438.00      1520675.02      6809337.96
      1523303.72      6808841.37      1525401.38      6811580.53
      1527230.19      6810637.51      1530894.49      6811986.78
      1532305.00      6810788.00      1534644.49      6811578.19
      1535360.09      6814682.98      1539151.57      6816389.57
      1538691.67      6818224.59      1542049.55      6818735.55
      1541756.61      6820331.98      1542604.96      6820574.23
      1541605.46      6822324.28      1542956.38      6825276.46
      1544615.00      6825498.63      1545856.65      6827284.90
      1547096.39      6826590.96      1547706.46      6828284.46
      1553394.48      6828478.21      1553455.00      6831738.00
      1560406.56      6841034.24      1567168.22      6841851.62
      1568454.62      6845153.27      1568202.83      6847582.55
      1566204.79      6848512.90      1566306.22      6850777.50
      1568121.65      6855104.67      1571605.00      6858688.00

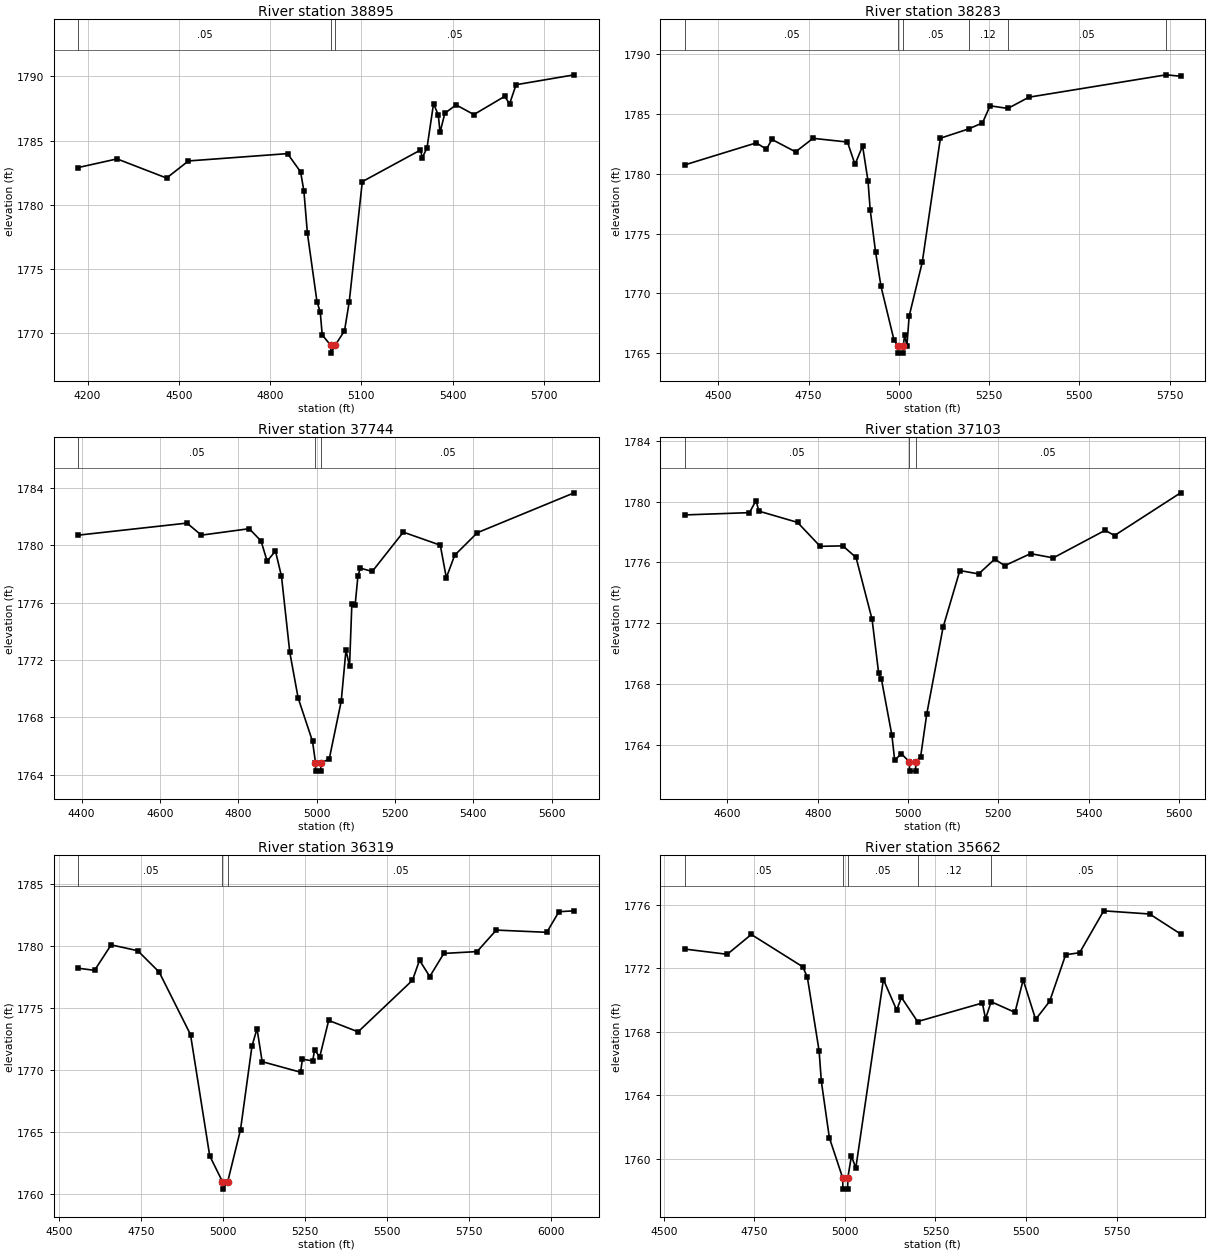
Type RM Length L Ch R = 1,38895,612,612,612
BEGIN DESCRIPTION:
Little Elm Creek 40758.895
END DESCRIPTION:
XS GIS Cut Line= 4
      1552889.99      6832086.02      1553372.22      6832178.04
      1553692.15      6832051.02      1554376.54      6831647.20
#Sta/Elev= 30
  4169.8 1782.90  4297.1 1783.57  4459.9 1782.08  4531.7 1783.41  4857.4 1783.98
  4900.4 1782.56  4911.2 1781.08  4922.8 1777.78  4954.2 1772.47  4965.0 1771.66
  4971.4 1769.88  4999.6 1769.06  4999.9 1768.46  5013.6 1769.06  5044.7 1770.19
  5060.3 1772.46  5103.2 1781.80  5294.5 1784.26  5300.3 1783.66  5315.9 1784.42
  5337.4 1787.87  5353.0 1786.98  5358.8 1785.63  5374.5 1787.12  5411.6 1787.77
  5470.1 1787.02  5571.6 1788.44  5587.2 1787.84  5608.7 1789.34  5799.6 1790.11
#Mann=3,-1,0
  4169.8    0.05       0  4999.6    0.05       0  5013.6    0.05       0
Bank Sta=4999.6,5013.6
Exp/Cntr=0.3,0.1

Type RM Length L Ch R = 1,38283,539,539,539
BEGIN DESCRIPTION:
Mapping XS cc6463bc
END DESCRIPTION:
XS GIS Cut Line= 2
      1553561.38      6832879.25      1554696.45      6832105.87
#Sta/Elev= 30
  4407.1 1780.75  4605.1 1782.59  4633.3 1782.06  4648.3 1782.88  4714.0 1781.84
  4762.4 1782.97  4857.7 1782.66  4878.6 1780.79  4899.6 1782.33  4914.6 1779.41
  4920.6 1777.01  4935.5 1773.48  4950.5 1770.60  4986.4 1766.13  4998.1 1765.61
  4998.5 1765.01  5011.8 1765.01  5012.1 1765.61  5016.2 1766.53  5022.3 1765.61
  5028.6 1768.10  5064.9 1772.61  5115.1 1782.98  5193.7 1783.76  5231.7 1784.26
  5252.7 1785.69  5302.0 1785.47  5360.4 1786.41  5740.5 1788.28  5780.6 1788.16
#Mann=6,-1,0
  4407.1    0.05       0  4998.1    0.05       0  5012.1    0.05       0
  5193.7    0.12       0  5302.0    0.05       0  5740.5    0.12       0
Bank Sta=4998.1,5012.1
Exp/Cntr=0.3,0.1

Type RM Length L Ch R = 1,37744,641,641,641
BEGIN DESCRIPTION:
Mapping XS a21781ca
END DESCRIPTION:
XS GIS Cut Line= 2
      1553853.81      6833298.64      1554930.56      6832633.36
#Sta/Elev= 30
  4391.5 1780.70  4668.9 1781.54  4705.5 1780.70  4827.8 1781.15  4858.0 1780.29
  4873.4 1778.89  4894.7 1779.59  4910.1 1777.83  4931.3 1772.53  4952.6 1769.35
  4989.3 1766.33  4996.9 1764.85  4997.2 1764.25  5010.5 1764.25  5010.9 1764.85
  5031.8 1765.07  5062.6 1769.13  5074.7 1772.69  5083.8 1771.57  5089.7 1775.88
  5098.2 1775.85  5105.1 1777.82  5111.0 1778.40  5141.8 1778.17  5221.0 1780.91
  5315.5 1780.00  5330.9 1777.73  5352.2 1779.30  5410.1 1780.87  5657.2 1783.65
#Mann=3,-1,0
  4391.5    0.05       0  4996.9    0.05       0  5010.9    0.05       0
Bank Sta=4996.9,5010.9
Exp/Cntr=0.3,0.1

Type RM Length L Ch R = 1,37103,784,784,784
BEGIN DESCRIPTION:
Mapping XS d2376857
END DESCRIPTION:
XS GIS Cut Line= 2
      1554353.99      6833787.28      1555238.97      6833137.01
#Sta/Elev= 30
  4505.6 1779.12  4648.7 1779.27  4663.4 1780.06  4669.6 1779.37  4755.3 1778.63
  4805.4 1777.06  4855.6 1777.09  4884.9 1776.33  4920.4 1772.27  4935.0 1768.73
  4941.2 1768.33  4964.3 1764.66  4970.5 1763.02  4985.2 1763.46  5003.2 1762.91
  5003.5 1762.31  5016.8 1762.31  5017.2 1762.91  5028.0 1763.26  5041.5 1766.06
  5077.7 1771.75  5114.8 1775.47  5156.5 1775.25  5192.0 1776.22  5214.2 1775.79
  5271.4 1776.58  5321.6 1776.30  5436.5 1778.11  5457.4 1777.77  5603.8 1780.57
#Mann=3,-1,0
  4505.6    0.05       0  5003.2    0.05       0  5017.2    0.05       0
Bank Sta=5003.2,5017.2
Exp/Cntr=0.3,0.1

Type RM Length L Ch R = 1,36319,657,657,657
BEGIN DESCRIPTION:
Mapping XS 17f3ca1d
END DESCRIPTION:
XS GIS Cut Line= 2
      1554838.81      6834349.02      1556141.59      6833580.42
#Sta/Elev= 30
  4559.5 1778.21  4609.0 1778.04  4659.6 1780.09  4740.8 1779.62  4806.1 1777.90
  4901.7 1772.87  4960.3 1763.11  4999.2 1761.03  4999.6 1760.43  5015.2 1761.03
  5054.3 1765.22  5089.2 1771.94  5104.6 1773.35  5120.3 1770.69  5237.4 1769.84
  5243.2 1770.89  5274.5 1770.75  5280.3 1771.64  5295.9 1771.07  5323.2 1774.01
  5413.0 1773.09  5578.8 1777.24  5600.3 1778.85  5631.6 1777.54  5674.5 1779.40
  5775.9 1779.55  5834.5 1781.28  5988.6 1781.10  6025.7 1782.76  6072.1 1782.83
#Mann=3,-1,0
  4559.5    0.05       0  4999.2    0.05       0  5015.2    0.05       0
Bank Sta=4999.2,5015.2
Exp/Cntr=0.3,0.1

Type RM Length L Ch R = 1,35662,584,584,584
BEGIN DESCRIPTION:
Mapping XS 8efcd69f
END DESCRIPTION:
XS GIS Cut Line= 2
      1555215.85      6834856.91      1556430.87      6834226.34
#Sta/Elev= 30
  4557.9 1773.21  4675.1 1772.88  4741.5 1774.13  4883.7 1772.09  4896.3 1771.43
  4928.7 1766.79  4934.9 1764.87  4957.0 1761.32  4993.9 1758.78  4994.3 1758.08
  5007.6 1758.08  5007.9 1758.78  5017.8 1760.16  5030.1 1759.42  5106.2 1771.29
  5142.8 1769.37  5156.1 1770.16  5200.5 1768.64  5379.4 1769.81  5388.2 1768.82
  5403.7 1769.89  5469.5 1769.22  5492.1 1771.27  5526.5 1768.78  5565.1 1769.91
  5609.4 1772.85  5648.0 1772.98  5714.4 1775.62  5841.3 1775.42  5926.8 1774.16
#Mann=5,-1,0
  4557.9    0.05       0  4993.9    0.03       0  5007.9    0.05       0
  5200.5    0.12       0  5403.7    0.05       0
Bank Sta=4993.9,5007.9
Exp/Cntr=0.3,0.1

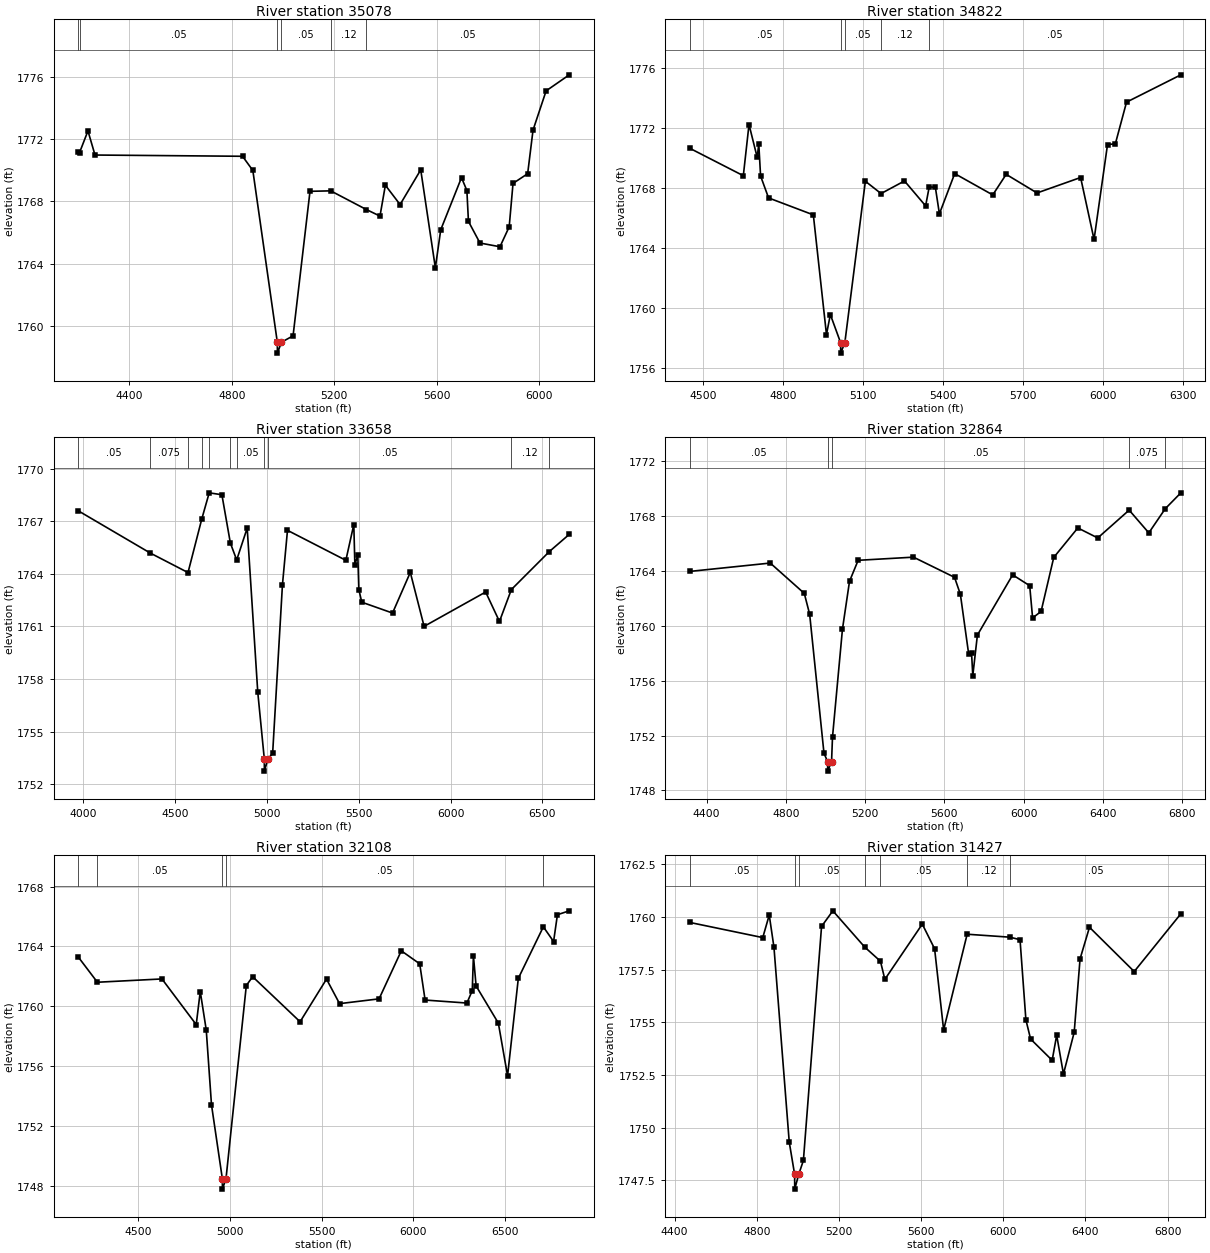
Type RM Length L Ch R = 1,35078,256,256,256
BEGIN DESCRIPTION:
Mapping XS 5ea4de76
END DESCRIPTION:
XS GIS Cut Line= 3
      1555166.78      6835230.46      1555917.68      6835147.99
      1556884.26      6834502.16
#Sta/Elev= 30
  4199.5 1771.15  4205.0 1771.13  4238.0 1772.53  4265.5 1770.98  4841.6 1770.90
  4881.8 1769.99  4977.4 1758.96  4977.8 1758.26  4993.4 1758.96  5038.9 1759.37
  5105.0 1768.65  5185.9 1768.68  5325.1 1767.48  5378.3 1767.06  5399.3 1769.04
  5456.8 1767.80  5537.4 1770.03  5594.5 1763.74  5615.5 1766.18  5696.6 1769.53
  5717.6 1768.70  5723.7 1766.72  5768.7 1765.33  5846.8 1765.09  5882.8 1766.37
  5897.8 1769.16  5954.9 1769.78  5975.9 1772.58  6027.0 1775.10  6117.4 1776.13
#Mann=6,-1,0
  4199.5   0.075       0  4205.0    0.05       0  4977.4    0.05       0
  4993.4    0.05       0  5185.9    0.12       0  5325.1    0.05       0
Bank Sta=4977.4,4993.4
Exp/Cntr=0.3,0.1

Type RM Length L Ch R = 1,34822,1164,1164,1164
BEGIN DESCRIPTION:
Mapping XS a2aa30bf
END DESCRIPTION:
XS GIS Cut Line= 4
      1555639.06      6835618.76      1556466.33      6835107.00
      1556574.06      6835030.05      1557172.68      6834602.47
#Sta/Elev= 30
  4449.3 1770.64  4650.3 1768.81  4671.6 1772.22  4702.3 1770.03  4708.2 1770.94
  4715.0 1768.79  4744.9 1767.33  4912.7 1766.20  4961.9 1758.23  4976.5 1759.56
  5014.8 1757.69  5015.2 1756.99  5030.8 1757.69  5107.7 1768.44  5166.5 1767.62
  5254.3 1768.46  5333.5 1766.80  5347.1 1768.07  5370.1 1768.03  5385.2 1766.27
  5442.5 1768.95  5585.1 1767.53  5635.4 1768.90  5751.0 1767.66  5914.4 1768.69
  5964.8 1764.56  6015.2 1770.88  6044.7 1770.94  6086.5 1773.71  6290.1 1775.53
#Mann=5,-1,0
  4449.3    0.05       0  5014.8    0.03       0  5030.8    0.05       0
  5166.5    0.12       0  5347.1    0.05       0
Bank Sta=5014.8,5030.8
Exp/Cntr=0.3,0.1

Type RM Length L Ch R = 1,33658,794,794,794
BEGIN DESCRIPTION:
Mapping XS 96bdc02a
END DESCRIPTION:
XS GIS Cut Line= 4
      1555833.34      6836552.95      1556388.94      6836496.53
      1557044.33      6836127.60      1558234.04      6835457.90
#Sta/Elev= 30
  3970.8 1767.60  4364.6 1765.18  4569.6 1764.07  4644.4 1767.12  4685.0 1768.62
  4754.2 1768.51  4800.4 1765.75  4834.8 1764.79  4892.0 1766.61  4949.6 1757.24
  4985.2 1753.44  4985.7 1752.74  5005.2 1753.44  5030.6 1753.75  5084.1 1763.38
  5111.5 1766.48  5429.5 1764.77  5472.8 1766.81  5478.6 1764.51  5494.5 1765.07
  5500.2 1763.10  5516.2 1762.38  5683.8 1761.76  5780.6 1764.08  5855.8 1761.00
  6191.1 1762.96  6266.3 1761.28  6331.1 1763.10  6538.2 1765.27  6646.6 1766.25
#Mann=11,-1,0
  3970.8    0.05       0  4364.6   0.075       0  4569.6    0.05       0
  4644.4   0.075       0  4685.0    0.05       0  4800.4   0.075       0
  4834.8    0.05       0  4985.2    0.03       0  5005.2    0.05       0
  6331.1    0.12       0  6538.2    0.05       0
Bank Sta=4985.2,5005.2
Exp/Cntr=0.3,0.1

Type RM Length L Ch R = 1,32864,756,756,756
BEGIN DESCRIPTION:
Mapping XS c2384eaa
END DESCRIPTION:
XS GIS Cut Line= 3
      1556714.43      6837303.84      1557517.42      6836726.56
      1558728.07      6835856.20
#Sta/Elev= 30
  4314.4 1763.97  4721.2 1764.58  4893.0 1762.37  4920.1 1760.85  4992.5 1750.71
  5010.7 1750.11  5011.2 1749.41  5030.7 1750.11  5035.5 1751.90  5085.8 1759.77
  5121.4 1763.25  5164.9 1764.78  5444.3 1765.01  5651.7 1763.54  5681.2 1762.30
  5722.9 1757.96  5737.7 1758.01  5743.8 1756.37  5767.1 1759.33  5945.1 1763.72
  6031.1 1762.93  6045.8 1760.58  6088.6 1761.05  6152.6 1764.99  6274.2 1767.14
  6374.8 1766.41  6533.3 1768.44  6632.6 1766.78  6715.5 1768.54  6794.4 1769.70
#Mann=5,-1,0
  4314.4    0.05       0  5010.7    0.05       0  5030.7    0.05       0
  6533.3   0.075       0  6715.5    0.05       0
Bank Sta=5010.7,5030.7
Exp/Cntr=0.3,0.1

Type RM Length L Ch R = 1,32108,681,681,681
BEGIN DESCRIPTION:
Mapping XS 7d84a11b
END DESCRIPTION:
XS GIS Cut Line= 3
      1557058.76      6837774.72      1558182.78      6837263.02
      1559348.75      6836412.38
#Sta/Elev= 30
  4171.4 1763.31  4276.6 1761.61  4628.7 1761.83  4815.5 1758.78  4837.5 1760.99
  4870.2 1758.42  4898.8 1753.42  4957.9 1748.49  4958.4 1747.79  4977.9 1748.49
  5088.7 1761.39  5123.2 1761.98  5381.9 1758.97  5526.0 1761.82  5597.1 1760.18
  5812.6 1760.50  5933.8 1763.71  6034.2 1762.84  6063.6 1760.42  6291.5 1760.22
  6320.8 1761.05  6327.0 1763.38  6341.7 1761.36  6463.0 1758.88  6513.2 1755.36
  6571.9 1761.87  6708.3 1765.31  6764.2 1764.33  6785.1 1766.12  6849.7 1766.38
#Mann=5,-1,0
  4171.4   0.075       0  4276.6    0.05       0  4957.9    0.03       0
  4977.9    0.05       0  6708.3   0.075       0
Bank Sta=4957.9,4977.9
Exp/Cntr=0.3,0.1

Type RM Length L Ch R = 1,31427,609,609,609
BEGIN DESCRIPTION:
Mapping XS 1e8ece6f
END DESCRIPTION:
XS GIS Cut Line= 3
      1557821.73      6838126.52      1558516.20      6837807.06
      1559994.30      6837127.14
#Sta/Elev= 30
  4473.1 1759.74  4828.9 1759.02  4860.4 1760.09  4883.4 1758.56  4957.8 1749.32
  4984.0 1747.79  4984.5 1747.09  5004.0 1747.79  5026.7 1748.45  5115.1 1759.55
  5170.1 1760.29  5325.3 1758.57  5401.8 1757.90  5423.3 1757.04  5605.6 1759.66
  5665.5 1758.49  5709.5 1754.64  5824.0 1759.18  6032.6 1759.04  6081.5 1758.92
  6110.0 1755.12  6132.9 1754.21  6237.9 1753.20  6259.9 1754.39  6292.9 1752.55
  6345.2 1754.53  6373.7 1758.01  6419.6 1759.51  6637.4 1757.41  6864.5 1760.15
#Mann=7,-1,0
  4473.1    0.05       0  4984.0    0.03       0  5004.0    0.05       0
  5325.3    0.12       0  5401.8    0.05       0  5824.0    0.12       0
  6032.6    0.05       0
Bank Sta=4984,5004
Exp/Cntr=0.3,0.1

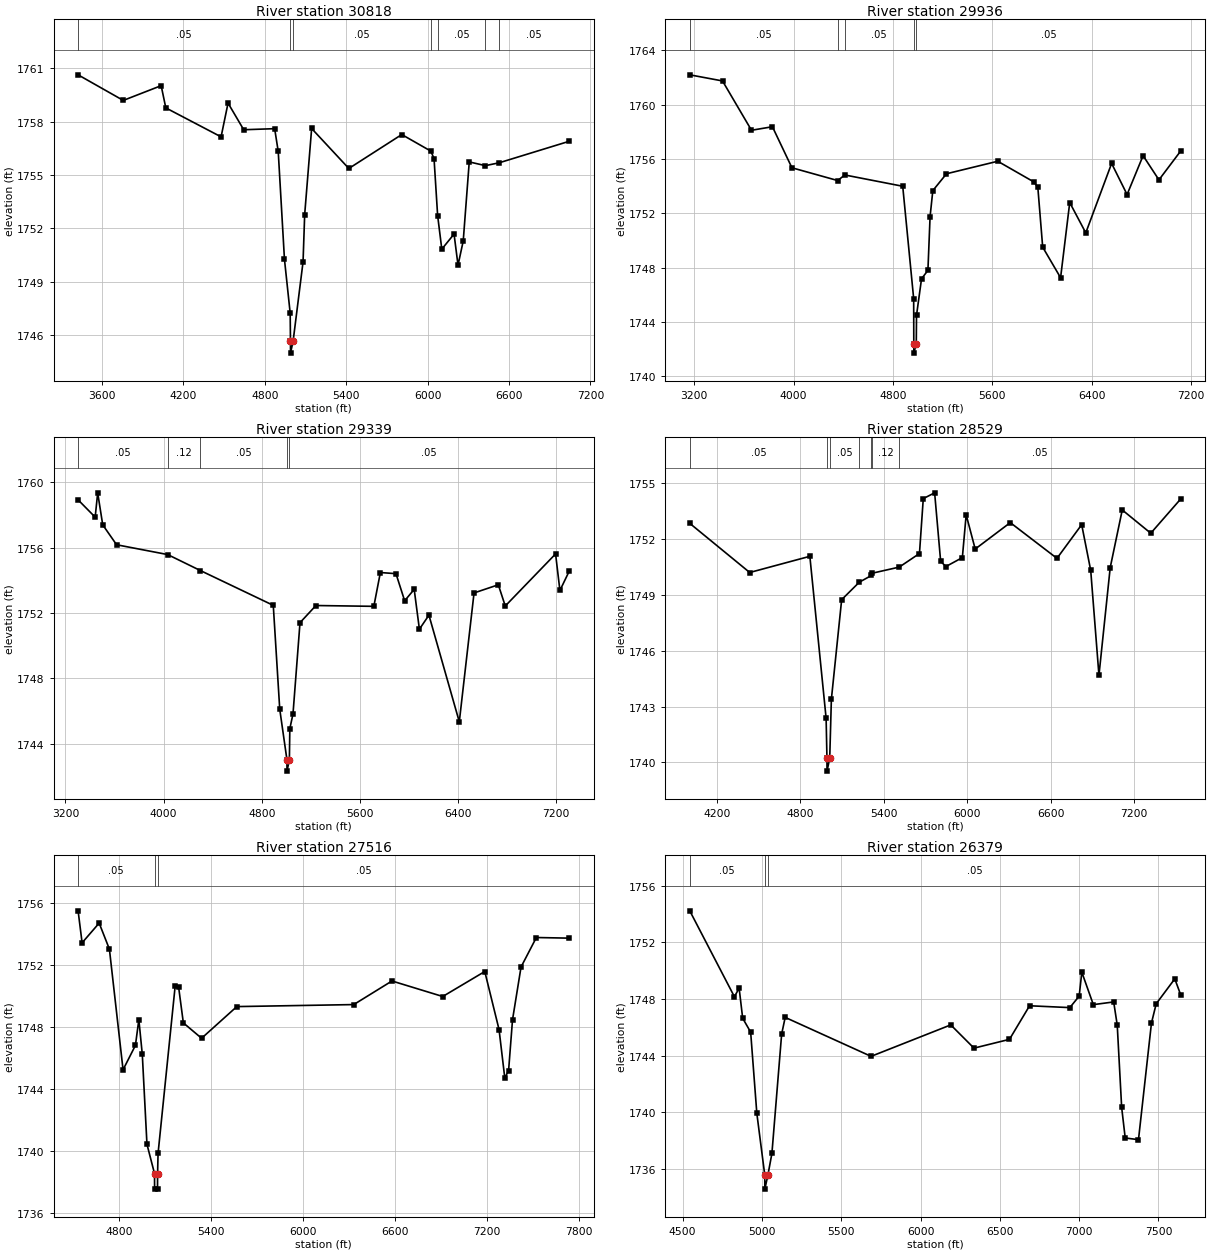
Type RM Length L Ch R = 1,30818,882,882,882
BEGIN DESCRIPTION:
Mapping XS e3458380
END DESCRIPTION:
XS GIS Cut Line= 4
      1557208.87      6838106.78      1558505.70      6838408.85
      1559635.12      6838031.67      1560607.31      6837524.75
#Sta/Elev= 30
  3424.6 1760.64  3757.5 1759.20  4036.7 1760.03  4070.9 1758.78  4478.2 1757.15
  4529.5 1759.05  4644.9 1757.55  4873.0 1757.61  4899.3 1756.33  4945.2 1750.26
  4987.4 1747.23  4989.4 1745.68  4989.9 1744.98  5009.4 1745.68  5082.2 1750.11
  5094.2 1752.78  5145.5 1757.62  5419.6 1755.37  5809.7 1757.28  6023.3 1756.35
  6047.4 1755.93  6073.9 1752.72  6104.6 1750.83  6194.9 1751.68  6224.1 1749.93
  6262.5 1751.29  6306.8 1755.74  6425.9 1755.53  6527.1 1755.69  7043.3 1756.90
#Mann=7,-1,0
  3424.6    0.05       0  4989.4    0.03       0  5009.4    0.05       0
  6023.3    0.12       0  6073.9    0.05       0  6425.9    0.12       0
  6527.1    0.05       0
Bank Sta=4989.4,5009.4
Exp/Cntr=0.3,0.1

Type RM Length L Ch R = 1,29936,597,597,597
BEGIN DESCRIPTION:
Mapping XS 91ab39cc
END DESCRIPTION:
XS GIS Cut Line= 5
      1557495.35      6839480.67      1558967.59      6839154.28
      1559566.46      6838877.60      1559781.74      6838721.35
      1561198.46      6838170.57
#Sta/Elev= 30
  3163.9 1762.19  3427.5 1761.74  3660.8 1758.11  3829.3 1758.37  3986.4 1755.35
  4354.8 1754.41  4412.2 1754.82  4878.3 1753.99  4966.5 1745.72  4967.5 1742.41
  4968.0 1741.71  4987.5 1742.41  4989.4 1744.49  5029.8 1747.18  5081.2 1747.80
  5098.6 1751.76  5120.7 1753.67  5230.8 1754.91  5643.4 1755.83  5933.7 1754.31
  5965.9 1753.93  6005.2 1749.51  6149.3 1747.26  6222.9 1752.79  6352.1 1750.56
  6560.1 1755.67  6684.7 1753.38  6813.5 1756.24  6941.1 1754.46  7117.6 1756.60
#Mann=5,-1,0
  3163.9    0.05       0  4354.8    0.12       0  4412.2    0.05       0
  4967.5    0.03       0  4987.5    0.05       0
Bank Sta=4967.5,4987.5
Exp/Cntr=0.3,0.1

Type RM Length L Ch R = 1,29339,810,810,810
BEGIN DESCRIPTION:
Mapping XS ccdd7270
END DESCRIPTION:
XS GIS Cut Line= 4
      1557849.54      6839973.73      1559058.00      6839689.49
      1560219.24      6839367.19      1561328.69      6838274.73
#Sta/Elev= 30
  3302.9 1758.92  3442.1 1757.86  3462.6 1759.35  3503.7 1757.39  3616.8 1756.17
  4033.1 1755.57  4300.1 1754.59  4894.1 1752.46  4946.8 1746.10  5005.4 1743.01
  5005.9 1742.31  5025.4 1743.01  5029.0 1744.91  5054.8 1745.81  5112.0 1751.40
  5241.7 1752.45  5713.9 1752.40  5767.1 1754.47  5894.4 1754.40  5965.1 1752.74
  6042.9 1753.44  6085.3 1751.00  6163.1 1751.86  6410.6 1745.33  6530.8 1753.22
  6728.8 1753.72  6785.3 1752.42  7195.5 1755.61  7230.9 1753.37  7306.5 1754.55
#Mann=5,-1,0
  3302.9    0.05       0  4033.1    0.12       0  4300.1    0.05       0
  5005.4    0.05       0  5025.4    0.05       0
Bank Sta=5005.4,5025.4
Exp/Cntr=0.3,0.1

Type RM Length L Ch R = 1,28529,1013,1013,1013
BEGIN DESCRIPTION:
Mapping XS db8ec915
END DESCRIPTION:
XS GIS Cut Line= 4
      1558833.78      6840398.44      1559677.57      6840388.02
      1560433.84      6839967.79      1561328.70      6838378.89
#Sta/Elev= 30
  4003.7 1752.84  4435.0 1750.20  4867.5 1751.07  4984.5 1742.37  4990.5 1740.23
  4991.0 1739.53  5010.5 1740.23  5022.3 1743.39  5096.3 1748.74  5223.2 1749.68
  5310.5 1750.04  5314.9 1750.16  5510.5 1750.49  5656.0 1751.22  5683.4 1754.17
  5765.1 1754.48  5808.4 1750.80  5846.0 1750.52  5964.5 1751.00  5991.9 1753.30
  6056.9 1751.46  6309.3 1752.88  6645.1 1750.96  6822.9 1752.77  6887.9 1750.31
  6947.1 1744.68  7028.0 1750.46  7114.7 1753.56  7319.9 1752.31  7536.3 1754.16
#Mann=7,-1,0
  4003.7    0.05       0  4990.5    0.05       0  5010.5    0.05       0
  5223.2    0.12       0  5310.5    0.05       0  5314.9    0.12       0
  5510.5    0.05       0
Bank Sta=4990.5,5010.5
Exp/Cntr=0.3,0.1

Type RM Length L Ch R = 1,27516,1137,1137,1137
BEGIN DESCRIPTION:
Mapping XS 4474bd50
END DESCRIPTION:
XS GIS Cut Line= 3
      1560255.70      6841471.35      1560548.35      6840894.66
      1561390.86      6838481.51
#Sta/Elev= 30
  4531.3 1755.48  4557.4 1753.42  4668.7 1754.69  4735.5 1753.01  4824.5 1745.24
  4905.1 1746.81  4927.5 1748.47  4950.0 1746.23  4980.4 1740.44  5029.7 1738.55
  5030.2 1737.55  5049.2 1737.55  5049.7 1738.55  5052.8 1739.85  5164.1 1750.61
  5186.7 1750.58  5217.7 1748.26  5336.7 1747.27  5566.4 1749.31  6329.0 1749.44
  6578.2 1750.96  6909.3 1749.96  7183.5 1751.57  7276.6 1747.83  7314.0 1744.71
  7338.8 1745.19  7364.5 1748.47  7420.0 1751.86  7519.8 1753.76  7734.0 1753.72
#Mann=3,-1,0
  4531.3    0.05       0  5029.7    0.03       0  5049.7    0.05       0
Bank Sta=5029.7,5049.7
Exp/Cntr=0.3,0.1

Type RM Length L Ch R = 1,26379,1161,1161,1161
BEGIN DESCRIPTION:
Mapping XS 0902fe9e
END DESCRIPTION:
XS GIS Cut Line= 2
      1561349.45      6841799.46      1562738.96      6839032.34
#Sta/Elev= 30
  4545.0 1754.23  4826.4 1748.17  4856.3 1748.77  4878.6 1746.65  4928.9 1745.67
  4967.9 1739.93  5017.8 1735.59  5018.3 1734.59  5037.8 1735.59  5062.9 1737.11
  5124.3 1745.53  5146.6 1746.71  5688.2 1743.96  6190.6 1746.18  6337.0 1744.54
  6560.8 1745.16  6687.5 1747.53  6941.3 1747.40  7000.2 1748.21  7016.9 1749.90
  7089.5 1747.61  7217.9 1747.80  7240.2 1746.17  7268.1 1740.36  7290.5 1738.20
  7374.2 1738.08  7456.0 1746.31  7485.9 1747.67  7603.1 1749.43  7641.4 1748.27
#Mann=3,-1,0
  4545.0    0.05       0  5017.8    0.03       0  5037.8    0.05       0
Bank Sta=5017.8,5037.8
Exp/Cntr=0.3,0.1

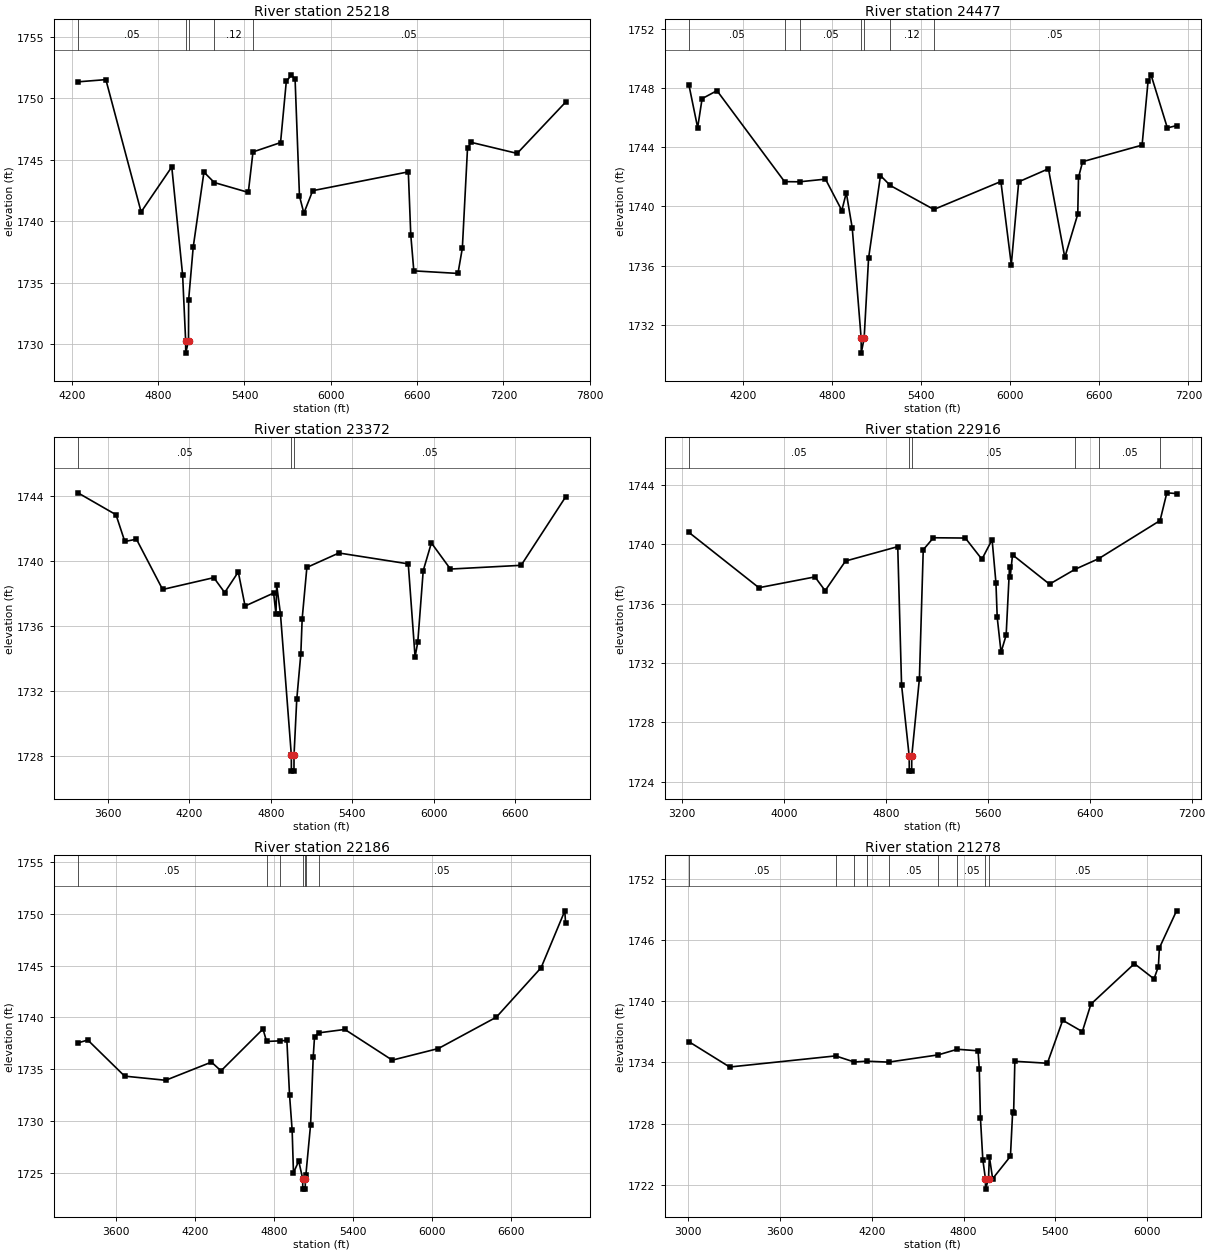
Type RM Length L Ch R = 1,25218,741,741,741
BEGIN DESCRIPTION:
Mapping XS aa368311
END DESCRIPTION:
XS GIS Cut Line= 2
      1562401.51      6842450.57      1563565.68      6839267.79
#Sta/Elev= 30
  4242.6 1751.33  4436.8 1751.51  4681.9 1740.75  4894.9 1744.41  4970.3 1735.62
  4991.3 1730.27  4991.8 1729.27  5011.3 1730.27  5012.0 1733.58  5043.9 1737.89
  5118.5 1743.99  5190.7 1743.14  5426.8 1742.34  5459.4 1745.63  5650.9 1746.39
  5690.9 1751.36  5726.8 1751.90  5752.0 1751.53  5782.5 1742.04  5813.0 1740.65
  5874.5 1742.48  6539.0 1744.01  6555.9 1738.91  6577.2 1735.96  6884.0 1735.75
  6914.5 1737.81  6950.4 1745.93  6975.6 1746.41  7295.4 1745.51  7631.6 1749.67
#Mann=5,-1,0
  4242.6    0.05       0  4991.3    0.03       0  5011.3    0.05       0
  5190.7    0.12       0  5459.4    0.05       0
Bank Sta=4991.3,5011.3
Exp/Cntr=0.3,0.1

Type RM Length L Ch R = 1,24477,1105,1105,1105
BEGIN DESCRIPTION:
Mapping XS f80ef36d
END DESCRIPTION:
XS GIS Cut Line= 3
      1563323.41      6842976.56      1563396.32      6841674.48
      1563507.10      6839696.30
#Sta/Elev= 30
  3834.1 1748.20  3892.8 1745.32  3922.8 1747.28  4023.0 1747.82  4478.4 1741.67
  4579.2 1741.66  4754.1 1741.84  4864.3 1739.72  4894.3 1740.92  4934.4 1738.54
  4994.5 1731.08  4995.0 1730.08  5014.5 1731.08  5044.6 1736.51  5124.7 1742.08
  5190.7 1741.41  5484.4 1739.79  5935.9 1741.68  6006.1 1736.06  6056.1 1741.66
  6256.4 1742.54  6366.6 1736.55  6453.9 1739.47  6458.9 1741.96  6486.8 1743.02
  6887.4 1744.14  6927.5 1748.45  6947.5 1748.89  7057.7 1745.30  7119.5 1745.46
#Mann=7,-1,0
  3834.1    0.05       0  4478.4    0.12       0  4579.2    0.05       0
  4994.5    0.05       0  5014.5    0.05       0  5190.7    0.12       0
  5484.4    0.05       0
Bank Sta=4994.5,5014.5
Exp/Cntr=0.3,0.1

Type RM Length L Ch R = 1,23372,456,456,456
BEGIN DESCRIPTION:
Mapping XS 82265f6b
END DESCRIPTION:
XS GIS Cut Line= 3
      1564016.12      6843221.34      1564526.53      6842523.44
      1564405.15      6839801.57
#Sta/Elev= 30
  3379.6 1744.22  3659.8 1742.87  3724.7 1741.22  3810.4 1741.36  4003.2 1738.26
  4379.8 1738.99  4459.9 1738.07  4560.0 1739.34  4610.0 1737.24  4820.2 1738.04
  4837.5 1736.73  4842.5 1738.54  4870.3 1736.77  4950.4 1728.06  4950.9 1727.06
  4969.9 1727.06  4970.4 1728.06  4990.4 1731.48  5020.4 1734.29  5030.4 1736.47
  5064.9 1739.62  5300.7 1740.51  5811.2 1739.84  5861.3 1734.11  5881.3 1735.01
  5921.3 1739.42  5981.4 1741.13  6121.5 1739.52  6642.0 1739.75  6968.8 1743.96
#Mann=3,-1,0
  3379.6    0.05       0  4950.4    0.05       0  4970.4    0.05       0
Bank Sta=4950.4,4970.4
Exp/Cntr=0.3,0.1

Type RM Length L Ch R = 1,22916,730,730,730
BEGIN DESCRIPTION:
Mapping XS 0866631e
END DESCRIPTION:
XS GIS Cut Line= 3
      1564935.47      6843497.16      1564949.36      6841774.94
      1564845.25      6839671.89
#Sta/Elev= 30
  3253.0 1740.81  3802.2 1737.08  4242.2 1737.81  4322.2 1736.88  4482.2 1738.88
  4892.2 1739.85  4922.2 1730.52  4982.2 1725.71  4982.7 1724.71  5001.7 1724.71
  5002.2 1725.71  5062.3 1730.95  5092.4 1739.64  5172.5 1740.45  5422.8 1740.43
  5552.9 1739.00  5633.0 1740.32  5663.1 1737.41  5673.1 1735.08  5703.1 1732.73
  5743.2 1733.88  5769.8 1738.45  5774.8 1737.77  5793.2 1739.30  6083.6 1737.32
  6283.8 1738.32  6469.8 1739.04  6951.6 1741.61  7004.7 1743.48  7080.9 1743.43
#Mann=6,-1,0
  3253.0    0.05       0  4982.2    0.05       0  5002.2    0.05       0
  6283.8   0.075       0  6469.8    0.05       0  6951.6   0.075       0
Bank Sta=4982.2,5002.2
Exp/Cntr=0.3,0.1

Type RM Length L Ch R = 1,22186,908,908,908
BEGIN DESCRIPTION:
Little Elm Creek 21500
END DESCRIPTION:
XS GIS Cut Line= 3
      1565331.30      6843372.20      1565678.53      6841962.44
      1565671.58      6839712.74
#Sta/Elev= 30
  3309.8 1737.54  3384.5 1737.82  3664.3 1734.34  3975.9 1733.94  4323.4 1735.69
  4396.1 1734.85  4714.8 1738.88  4742.0 1737.68  4844.2 1737.74  4896.1 1737.78
  4916.1 1732.56  4936.1 1729.13  4946.1 1725.02  4986.1 1726.16  5016.1 1724.45
  5016.6 1723.45  5035.6 1723.45  5036.1 1724.45  5040.1 1724.79  5076.1 1729.67
  5096.1 1736.20  5106.1 1738.13  5138.0 1738.51  5336.1 1738.84  5696.1 1735.88
  6046.1 1737.00  6486.1 1740.02  6826.1 1744.79  7006.1 1750.27  7011.4 1749.12
#Mann=7,-1,0
  3309.8    0.05       0  4742.0    0.12       0  4844.2    0.05       0
  5016.1    0.05       0  5036.1    0.05       0  5040.1    0.12       0
  5138.0    0.05       0
Bank Sta=5016.1,5036.1
Exp/Cntr=0.3,0.1

Type RM Length L Ch R = 1,21278,480,480,480
BEGIN DESCRIPTION:
Little Elm Creek 21000
END DESCRIPTION:
XS GIS Cut Line= 3
      1565560.46      6843406.91      1566636.86      6841608.28
      1567323.49      6840759.32
#Sta/Elev= 30
  3004.2 1736.02  3270.5 1733.54  3963.1 1734.63  4085.2 1734.03  4165.4 1734.11
  4309.8 1734.02  4634.2 1734.73  4759.0 1735.28  4894.5 1735.13  4902.5 1733.35
  4910.0 1728.56  4925.6 1724.46  4942.8 1722.57  4943.3 1721.57  4962.8 1722.57
  4968.4 1724.76  4989.8 1722.59  5106.2 1724.79  5120.6 1729.13  5127.0 1729.02
  5135.0 1734.10  5347.7 1733.91  5447.9 1738.12  5576.2 1737.01  5632.3 1739.70
  5916.8 1743.67  6044.8 1742.18  6073.5 1743.39  6080.0 1745.21  6192.2 1748.85
#Mann=9,-1,0
  3004.2    0.05       0  3963.1    0.12       0  4085.2    0.05       0
  4165.4    0.12       0  4309.8    0.05       0  4634.2    0.12       0
  4759.0    0.05       0  4942.8    0.05       0  4962.8    0.05       0
Bank Sta=4942.8,4962.8
Exp/Cntr=0.3,0.1

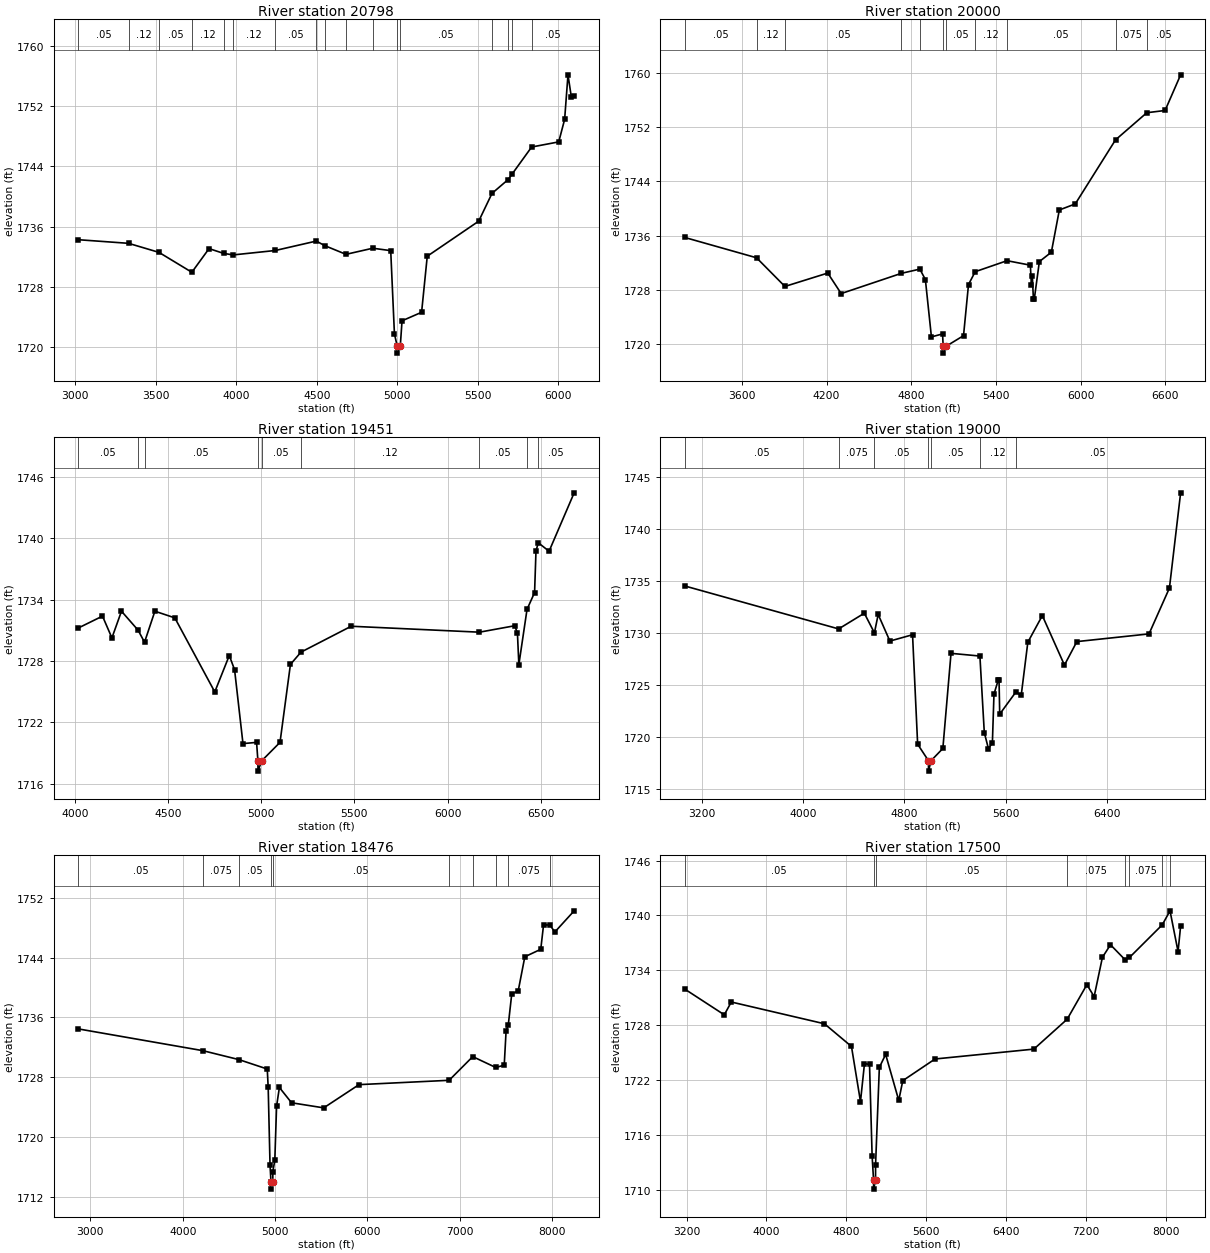
Type RM Length L Ch R = 1,20798,798,798,798
BEGIN DESCRIPTION:
Little Elm Creek 20500
END DESCRIPTION:
XS GIS Cut Line= 3
      1565768.79      6843316.63      1567032.69      6841809.67
      1567733.50      6840942.33
#Sta/Elev= 30
  3018.3 1734.26  3330.3 1733.78  3519.6 1732.58  3723.9 1729.94  3830.8 1733.08
  3920.7 1732.45  3980.1 1732.24  4242.7 1732.83  4497.6 1734.08  4549.1 1733.48
  4682.0 1732.32  4848.5 1733.13  4960.0 1732.81  4983.0 1721.78  4999.6 1720.21
  5000.1 1719.21  5019.6 1720.21  5030.4 1723.50  5151.9 1724.63  5187.1 1732.07
  5506.9 1736.72  5589.6 1740.41  5690.3 1742.25  5712.8 1742.92  5835.9 1746.56
  6004.3 1747.24  6041.0 1750.23  6061.8 1756.14  6082.6 1753.21  6100.2 1753.28
#Mann=17,-1,0
  3018.3    0.05       0  3330.3    0.12       0  3519.6    0.05       0
  3723.9    0.12       0  3920.7    0.05       0  3980.1    0.12       0
  4242.7    0.05       0  4497.6    0.12       0  4549.1    0.05       0
  4682.0    0.12       0  4848.5    0.05       0  4999.6    0.03       0
  5019.6    0.05       0  5589.6   0.075       0  5690.3    0.05       0
  5712.8   0.075       0  5835.9    0.05       0
Bank Sta=4999.6,5019.6
Exp/Cntr=0.3,0.1

Type RM Length L Ch R = 1,20000,549,549,549
BEGIN DESCRIPTION:
Little Elm Creek 20000
END DESCRIPTION:
XS GIS Cut Line= 3
      1565817.38      6843420.80      1567360.04      6842484.62
      1568539.63      6841247.17
#Sta/Elev= 30
  3195.5 1735.72  3704.0 1732.73  3905.1 1728.51  4208.7 1730.48  4303.7 1727.46
  4730.5 1730.44  4861.4 1731.06  4900.5 1729.53  4943.4 1721.08  5022.5 1721.52
  5026.6 1719.69  5027.1 1718.69  5046.6 1719.69  5170.9 1721.26  5206.2 1728.79
  5253.6 1730.68  5479.4 1732.30  5644.7 1731.64  5651.9 1728.76  5658.8 1729.98
  5666.0 1726.70  5672.9 1726.72  5708.5 1732.17  5793.4 1733.55  5850.0 1739.77
  5962.9 1740.66  6248.1 1750.09  6469.9 1754.09  6599.5 1754.42  6709.6 1759.67
#Mann=11,-1,0
  3195.5    0.05       0  3704.0    0.12       0  3905.1    0.05       0
  4730.5    0.12       0  4861.4    0.05       0  5026.6    0.03       0
  5046.6    0.05       0  5253.6    0.12       0  5479.4    0.05       0
  6248.1   0.075       0  6469.9    0.05       0
Bank Sta=5026.6,5046.6
Exp/Cntr=0.3,0.1

Type RM Length L Ch R = 1,19451,451,451,451
BEGIN DESCRIPTION:
Little Elm Creek 19500
END DESCRIPTION:
XS GIS Cut Line= 3
      1566636.89      6843441.60      1567560.47      6842990.22
      1568642.91      6841766.29
#Sta/Elev= 30
  4017.8 1731.23  4147.5 1732.39  4198.1 1730.26  4249.4 1732.87  4338.4 1731.02
  4373.2 1729.84  4428.8 1732.87  4535.8 1732.22  4750.3 1724.98  4828.2 1728.54
  4856.6 1727.15  4901.7 1719.93  4974.8 1720.05  4981.8 1718.24  4982.3 1717.24
  5001.8 1718.24  5100.5 1720.05  5156.5 1727.67  5213.1 1728.87  5482.7 1731.40
  6171.2 1730.82  6361.0 1731.45  6375.2 1730.71  6382.8 1727.65  6426.7 1733.05
  6467.2 1734.69  6474.8 1738.76  6487.1 1739.56  6545.0 1738.73  6679.7 1744.44
#Mann=9,-1,0
  4017.8    0.05       0  4338.4   0.075       0  4373.2    0.05       0
  4981.8    0.03       0  5001.8    0.05       0  5213.1    0.12       0
  6171.2    0.05       0  6426.7   0.075       0  6487.1    0.05       0
Bank Sta=4981.8,5001.8
Exp/Cntr=0.3,0.1

Type RM Length L Ch R = 1,19000,524,524,524
BEGIN DESCRIPTION:
Little Elm Creek 19000
END DESCRIPTION:
XS GIS Cut Line= 3
      1565726.30      6843632.58      1567650.04      6843441.65
      1569466.03      6842652.36
#Sta/Elev= 30
  3066.8 1734.51  4281.0 1730.38  4483.7 1731.89  4563.4 1730.00  4593.0 1731.77
  4685.5 1729.21  4864.3 1729.82  4904.5 1719.29  4990.0 1717.70  4990.5 1716.70
  5010.0 1717.70  5103.5 1718.88  5167.9 1728.03  5395.9 1727.77  5430.6 1720.41
  5463.4 1718.85  5494.5 1719.44  5507.0 1724.11  5539.7 1725.42  5546.8 1725.51
  5552.3 1722.18  5679.8 1724.31  5721.9 1723.99  5774.2 1729.10  5888.6 1731.66
  6063.1 1726.90  6161.2 1729.16  6730.6 1729.90  6891.7 1734.31  6980.1 1743.47
#Mann=7,-1,0
  3066.8    0.05       0  4281.0   0.075       0  4563.4    0.05       0
  4990.0    0.03       0  5010.0    0.05       0  5395.9    0.12       0
  5679.8    0.05       0
Bank Sta=4990,5010
Exp/Cntr=0.3,0.1

Type RM Length L Ch R = 1,18476,976,976,976
BEGIN DESCRIPTION:
Little Elm Creek 18000
END DESCRIPTION:
XS GIS Cut Line= 3
      1565703.72      6844084.84      1567787.03      6843939.01
      1571021.61      6843383.71
#Sta/Elev= 30
  2869.3 1734.46  4217.3 1731.55  4608.9 1730.35  4915.6 1729.09  4925.6 1726.63
  4945.6 1716.24  4955.8 1714.01  4956.3 1713.01  4975.8 1714.01  4975.9 1715.37
  4997.3 1716.86  5016.5 1724.11  5047.0 1726.62  5178.9 1724.57  5527.0 1723.89
  5909.4 1727.00  6885.3 1727.58  7141.2 1730.75  7389.9 1729.30  7482.1 1729.60
  7502.4 1734.19  7526.5 1735.04  7563.2 1739.10  7634.3 1739.59  7705.3 1744.12
  7877.8 1745.12  7908.2 1748.39  7977.3 1748.37  8030.0 1747.43  8239.6 1750.27
#Mann=10,-1,0
  2869.3    0.05       0  4217.3   0.075       0  4608.9    0.05       0
  4955.8    0.03       0  4975.8    0.05       0  6885.3   0.075       0
  7141.2     0.1       0  7389.9    0.05       0  7526.5   0.075       0
  7977.3     0.1       0
Bank Sta=4955.8,4975.8
Exp/Cntr=0.3,0.1

Type RM Length L Ch R = 1,17500,500,500,500
BEGIN DESCRIPTION:
Little Elm Creek 17500
END DESCRIPTION:
XS GIS Cut Line= 3
      1566460.68      6844675.12      1568274.02      6844800.85
      1571390.58      6844376.59
#Sta/Elev= 30
  3182.3 1731.95  3577.6 1729.14  3647.7 1730.54  4580.0 1728.16  4850.6 1725.68
  4940.8 1719.65  4980.9 1723.81  5031.3 1723.71  5057.4 1713.68  5071.7 1711.08
  5072.2 1710.08  5091.7 1711.08  5091.8 1712.73  5129.7 1723.39  5192.7 1724.81
  5323.9 1719.78  5364.3 1721.94  5687.3 1724.31  6676.3 1725.39  7009.8 1728.66
  7207.1 1732.44  7279.5 1731.13  7362.6 1735.43  7443.3 1736.80  7588.4 1735.17
  7633.4 1735.41  7961.5 1738.98  8039.1 1740.51  8119.5 1736.06  8145.3 1738.84
#Mann=8,-1,0
  3182.3    0.05       0  5071.7    0.03       0  5091.7    0.05       0
  7009.8   0.075       0  7588.4     0.1       0  7633.4   0.075       0
  7961.5     0.1       0  8039.1   0.075       0
Bank Sta=5071.7,5091.7
Exp/Cntr=0.3,0.1