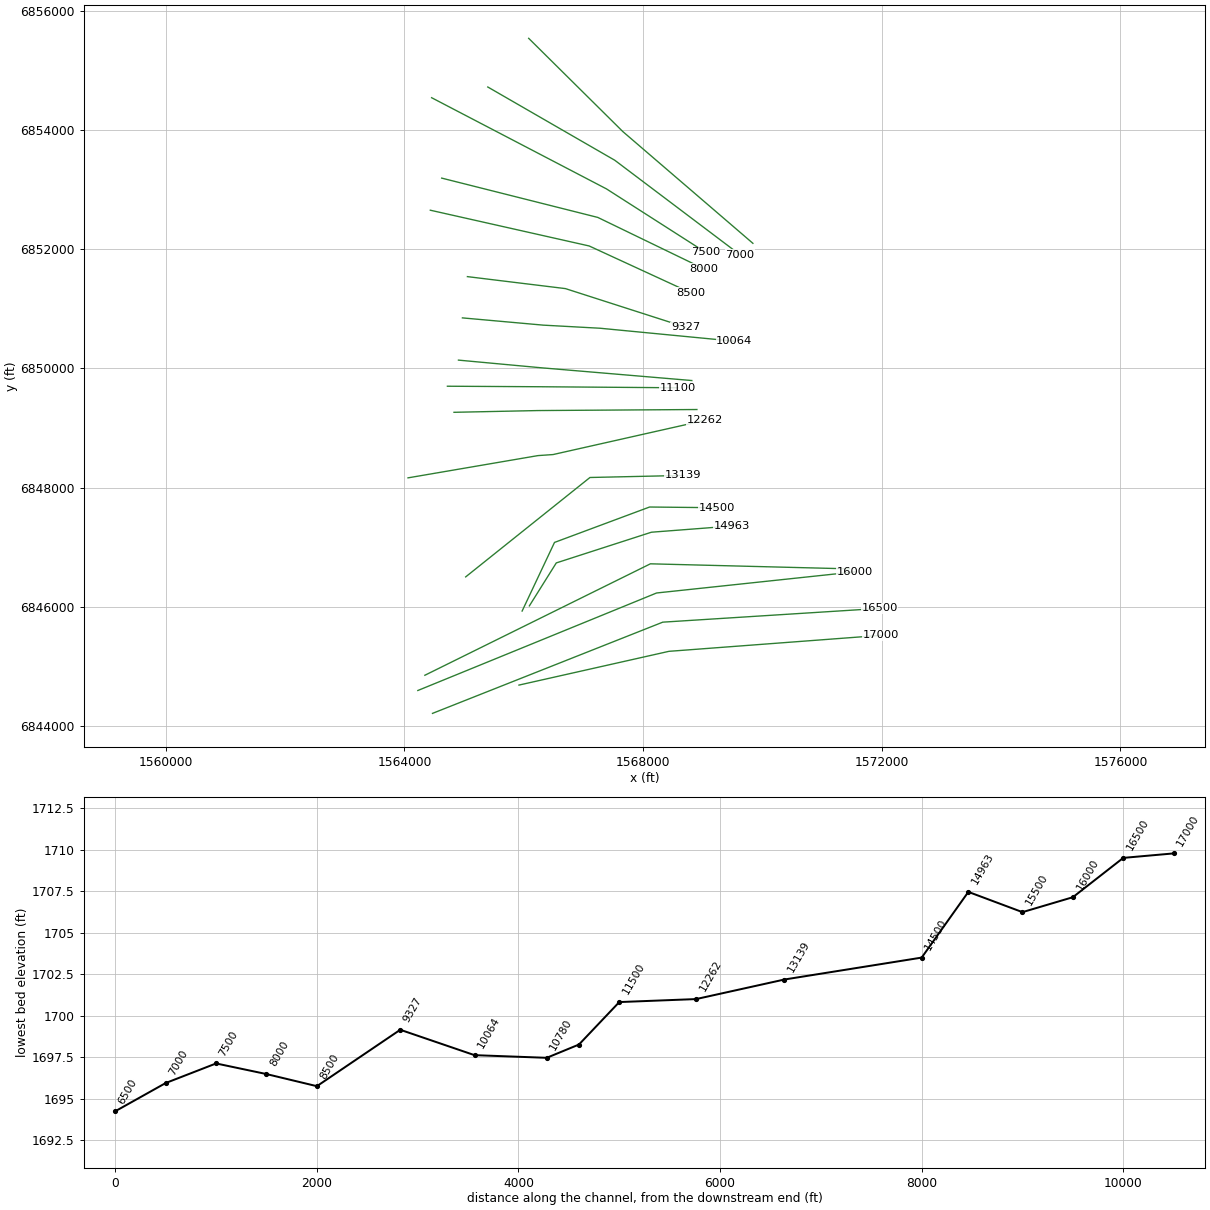
HEC-RAS study Little Elm Creek.prj: Little Elm Creek Base Level Engineering

--- Little Elm Creek.g01 (geometry) --- (continued)

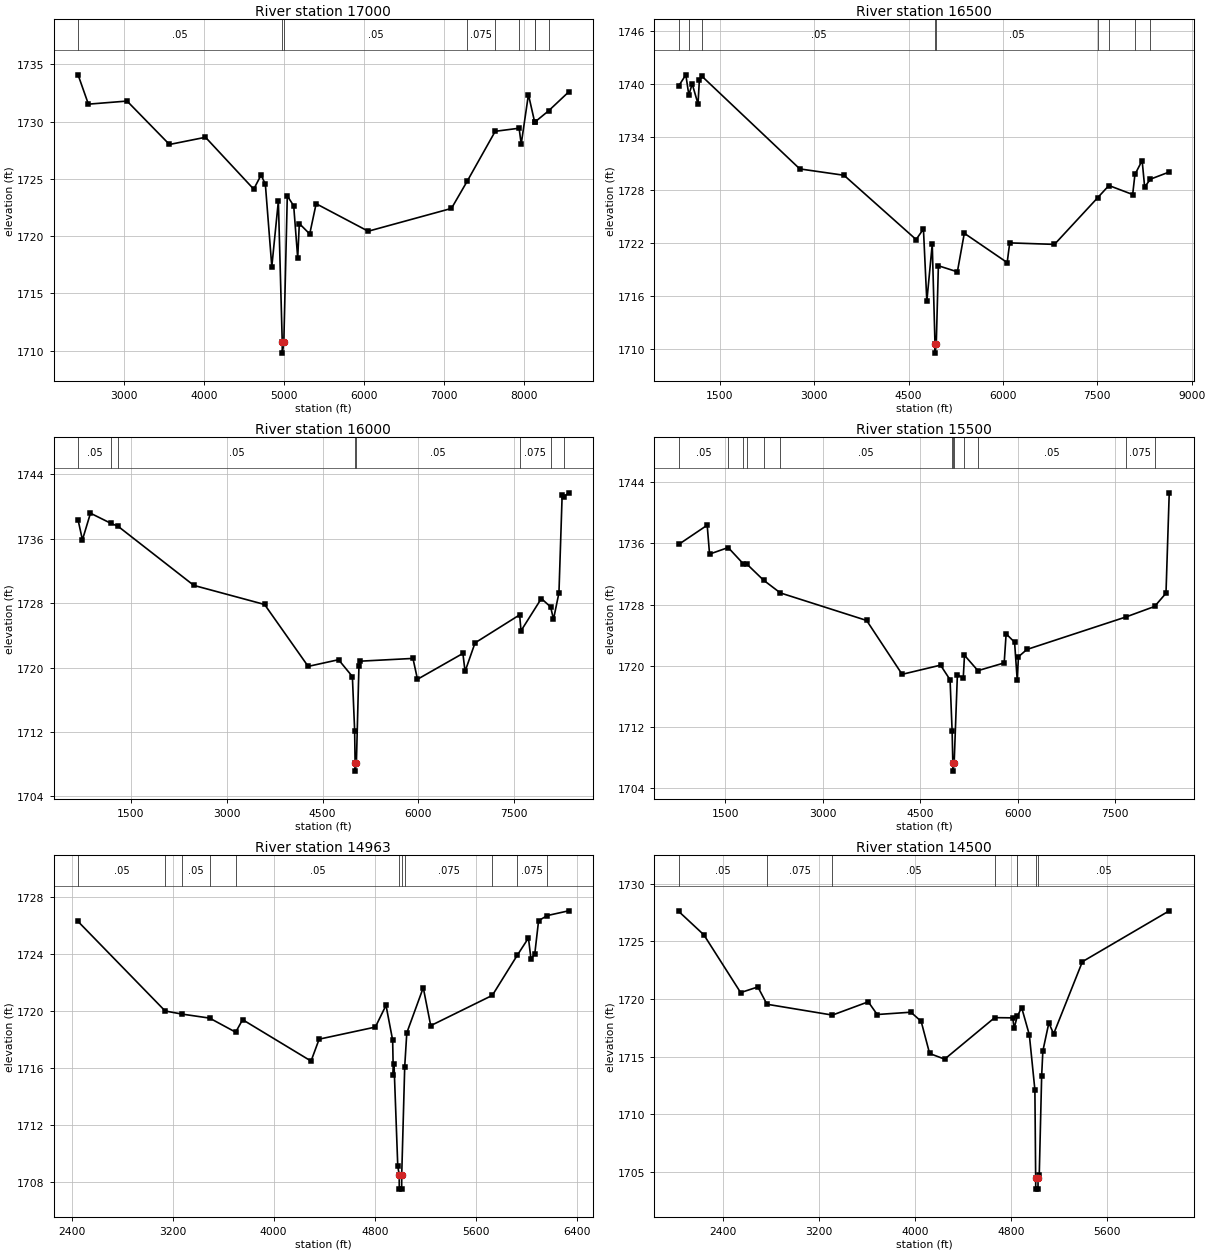
Type RM Length L Ch R = 1,17000,500,500,500
BEGIN DESCRIPTION:
Little Elm Creek 17000
END DESCRIPTION:
XS GIS Cut Line= 3
      1565918.99      6844689.01      1568433.07      6845255.02
      1571986.38      6845522.97
#Sta/Elev= 30
  2423.0 1734.08  2552.2 1731.52  3036.1 1731.79  3566.9 1728.00  4018.0 1728.63
  4622.1 1724.10  4713.7 1725.33  4767.3 1724.54  4848.2 1717.34  4930.2 1723.06
  4978.7 1710.79  4979.2 1709.79  4998.7 1710.79  5042.1 1723.52  5122.3 1722.64
  5172.4 1718.10  5192.5 1721.10  5322.8 1720.19  5403.1 1722.83  6054.9 1720.43
  7096.9 1722.42  7295.3 1724.81  7644.9 1729.15  7943.8 1729.42  7970.3 1728.04
  8060.6 1732.36  8139.1 1729.94  8141.5 1729.96  8313.3 1730.94  8563.4 1732.58
#Mann=9,-1,0
  2423.0    0.05       0  4978.7    0.03       0  4998.7    0.05       0
  7295.3   0.075       0  7644.9     0.1       0  7943.8   0.075       0
  8139.1     0.1       0  8141.5   0.075       0  8313.3    0.05       0
Bank Sta=4978.7,4998.7
Exp/Cntr=0.3,0.1

Type RM Length L Ch R = 1,16500,500,500,500
BEGIN DESCRIPTION:
Little Elm Creek 16500
END DESCRIPTION:
XS GIS Cut Line= 3
      1564469.75      6844214.69      1568329.46      6845744.16
      1571964.85      6845974.84
#Sta/Elev= 30
   848.3 1739.79   961.5 1741.05  1009.4 1738.76  1062.3 1740.03  1155.1 1737.75
  1176.6 1740.46  1220.0 1740.87  2772.5 1730.39  3474.9 1729.67  4620.5 1722.39
  4737.0 1723.58  4790.8 1715.40  4876.9 1721.86  4920.7 1710.52  4921.2 1709.52
  4940.7 1710.52  4974.4 1719.42  5276.1 1718.73  5386.3 1723.10  6067.7 1719.78
  6107.8 1722.01  6819.2 1721.84  7503.2 1727.11  7684.1 1728.51  8061.7 1727.49
  8097.4 1729.76  8212.0 1731.34  8252.1 1728.34  8344.0 1729.23  8642.7 1730.04
#Mann=9,-1,0
   848.3    0.05       0  1009.4   0.075       0  1220.0    0.05       0
  4920.7    0.05       0  4940.7    0.05       0  7503.2   0.075       0
  7684.1     0.1       0  8097.4   0.075       0  8344.0    0.05       0
Bank Sta=4920.7,4940.7
Exp/Cntr=0.3,0.1

Type RM Length L Ch R = 1,16000,500,500,500
BEGIN DESCRIPTION:
Little Elm Creek 16000
END DESCRIPTION:
XS GIS Cut Line= 3
      1564223.98      6844598.26      1568225.85      6846233.31
      1571555.01      6846588.00
#Sta/Elev= 30
   677.0 1738.35   745.4 1735.88   870.9 1739.19  1195.5 1737.91  1301.2 1737.57
  2487.5 1730.22  3593.6 1727.85  4275.3 1720.16  4750.6 1720.99  4966.7 1718.90
  5002.1 1712.19  5009.3 1708.15  5009.8 1707.15  5029.3 1708.15  5069.5 1720.24
  5093.1 1720.81  5914.3 1721.15  5984.7 1718.56  6694.9 1721.77  6728.9 1719.53
  6884.8 1723.08  7582.2 1726.56  7603.8 1724.58  7921.9 1728.59  8067.4 1727.54
  8111.8 1726.01  8197.1 1729.30  8247.4 1741.49  8277.0 1741.23  8348.0 1741.72
#Mann=8,-1,0
   677.0    0.05       0  1195.5   0.075       0  1301.2    0.05       0
  5009.3    0.05       0  5029.3    0.05       0  7582.2   0.075       0
  8067.4    0.05       0  8277.0   0.075       0
Bank Sta=5009.3,5029.3
Exp/Cntr=0.3,0.1

Type RM Length L Ch R = 1,15500,537,537,537
BEGIN DESCRIPTION:
Little Elm Creek 15500
END DESCRIPTION:
XS GIS Cut Line= 3
      1564341.92      6844853.92      1568122.24      6846722.46
      1571454.97      6846638.00
#Sta/Elev= 30
   783.1 1735.88  1221.6 1738.39  1257.8 1734.61  1544.7 1735.47  1778.6 1733.33
  1833.0 1733.30  2088.4 1731.21  2347.2 1729.54  3675.6 1725.94  4222.2 1718.90
  4813.4 1720.10  4960.1 1718.19  4991.6 1711.51  5002.8 1707.25  5003.3 1706.25
  5022.8 1707.25  5072.8 1718.86  5162.8 1718.39  5182.1 1721.39  5388.8 1719.38
  5793.0 1720.39  5823.0 1724.19  5953.1 1723.10  5993.1 1718.22  6013.1 1721.20
  6143.1 1722.15  7668.0 1726.40  8108.5 1727.77  8283.8 1729.50  8333.8 1742.62
#Mann=13,-1,0
   783.1    0.05       0  1544.7   0.075       0  1778.6     0.1       0
  1833.0    0.05       0  2088.4    0.12       0  2347.2    0.05       0
  4991.6   0.075       0  5002.8    0.05       0  5022.8   0.075       0
  5182.1     0.1       0  5388.8    0.05       0  7668.0   0.075       0
  8108.5    0.05       0
Bank Sta=5002.8,5022.8
Exp/Cntr=0.3,0.1

Type RM Length L Ch R = 1,14963,463,463,463
BEGIN DESCRIPTION:
Mapping XS 79cf01be
END DESCRIPTION:
XS GIS Cut Line= 4
      1566093.45      6846017.11      1566544.85      6846737.62
      1568139.47      6847252.37      1569491.80      6847356.40
#Sta/Elev= 30
  2451.9 1726.28  3141.2 1719.99  3275.9 1719.77  3493.1 1719.49  3699.3 1718.50
  3754.1 1719.38  4295.8 1716.47  4359.8 1718.01  4804.9 1718.86  4889.0 1720.39
  4941.6 1717.94  4947.0 1715.49  4952.3 1716.28  4982.1 1709.09  4993.4 1708.47
  4993.9 1707.47  5012.9 1707.47  5013.4 1708.47  5037.1 1716.08  5053.5 1718.45
  5183.9 1721.63  5242.9 1718.96  5730.6 1721.09  5928.8 1723.92  6016.4 1725.12
  6036.4 1723.63  6066.5 1724.01  6096.6 1726.34  6166.5 1726.70  6334.1 1727.03
#Mann=11,-1,0
  2451.9    0.05       0  3141.2   0.075       0  3275.9    0.05       0
  3493.1   0.075       0  3699.3    0.05       0  4993.4    0.03       0
  5013.4    0.05       0  5037.1   0.075       0  5730.6    0.05       0
  5928.8   0.075       0  6166.5    0.05       0
Bank Sta=4993.4,5013.4
Exp/Cntr=0.3,0.1

Type RM Length L Ch R = 1,14500,1361,1361,1361
BEGIN DESCRIPTION:
Little Elm Creek 14500
END DESCRIPTION:
XS GIS Cut Line= 4
      1565971.93      6845930.31      1566514.74      6847081.12
      1568108.52      6847674.91      1569229.95      6847663.00
#Sta/Elev= 30
  2026.8 1727.59  2236.6 1725.56  2543.9 1720.55  2687.6 1721.04  2763.5 1719.54
  3309.7 1718.60  3609.0 1719.75  3683.7 1718.65  3964.9 1718.85  4050.6 1718.06
  4121.2 1715.27  4246.9 1714.78  4664.6 1718.38  4814.8 1718.36  4826.7 1717.47
  4853.0 1718.49  4889.5 1719.25  4953.6 1716.89  5000.0 1712.12  5006.5 1704.51
  5007.0 1703.51  5026.0 1703.51  5026.5 1704.51  5036.5 1704.76  5056.5 1713.33
  5066.5 1715.49  5116.5 1717.92  5156.5 1716.97  5396.5 1723.23  6121.5 1727.64
#Mann=7,-1,0
  2026.8    0.05       0  2763.5   0.075       0  3309.7    0.05       0
  4664.6    0.12       0  4853.0    0.05       0  5006.5    0.03       0
  5026.5    0.05       0
Bank Sta=5006.5,5026.5
Exp/Cntr=0.3,0.1

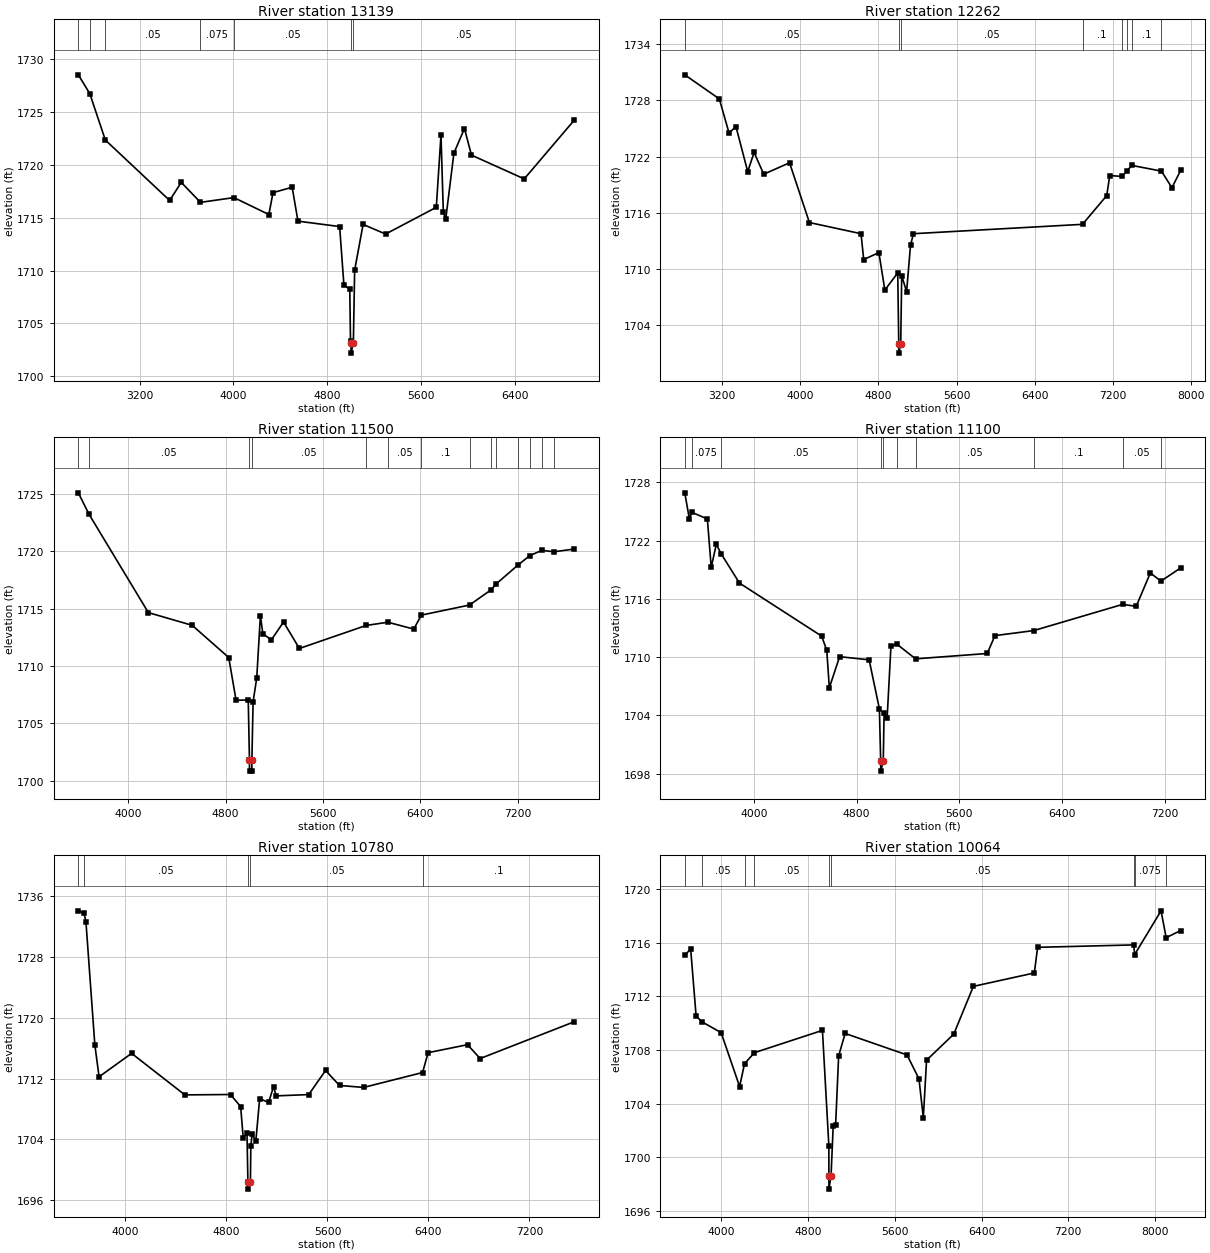
Type RM Length L Ch R = 1,13139,877,877,877
BEGIN DESCRIPTION:
Little Elm Creek 13292.064
END DESCRIPTION:
XS GIS Cut Line= 3
      1565025.79      6846503.27      1567109.08      6848169.91
      1568670.78      6848204.61
#Sta/Elev= 30
  2677.3 1728.53  2775.1 1726.75  2907.5 1722.36  3456.2 1716.64  3555.4 1718.35
  3719.3 1716.46  4004.6 1716.91  4302.7 1715.31  4338.2 1717.38  4501.5 1717.89
  4551.1 1714.68  4906.5 1714.17  4943.0 1708.64  4992.9 1708.23  4999.3 1703.32
  5003.7 1703.19  5004.2 1702.19  5023.7 1703.19  5034.5 1710.03  5106.6 1714.37
  5298.7 1713.46  5731.2 1715.99  5771.2 1722.84  5791.2 1715.53  5811.3 1714.84
  5881.3 1721.11  5971.3 1723.45  6031.3 1720.93  6481.4 1718.68  6907.3 1724.23
#Mann=7,-1,0
  2677.3    0.05       0  2775.1   0.075       0  2907.5    0.05       0
  3719.3   0.075       0  4004.6    0.05       0  5003.7    0.03       0
  5023.7    0.05       0
Bank Sta=5003.7,5023.7
Exp/Cntr=0.3,0.1

Type RM Length L Ch R = 1,12262,762,762,762
BEGIN DESCRIPTION:
Little Elm Creek 12500
END DESCRIPTION:
XS GIS Cut Line= 4
      1564059.58      6848163.83      1566238.42      6848537.10
      1566490.16      6848554.46      1569031.76      6849126.97
#Sta/Elev= 30
  2822.7 1730.72  3175.7 1728.15  3274.6 1724.52  3345.6 1725.19  3465.8 1720.39
  3530.9 1722.43  3629.7 1720.11  3893.5 1721.33  4096.4 1714.95  4624.0 1713.76
  4651.5 1711.00  4806.6 1711.74  4867.5 1707.75  4999.4 1709.57  5009.7 1702.01
  5010.2 1701.01  5029.7 1702.01  5039.9 1709.27  5090.0 1707.58  5130.1 1712.55
  5160.2 1713.76  6888.0 1714.76  7135.7 1717.83  7166.4 1719.97  7291.3 1719.87
  7343.8 1720.48  7392.2 1721.05  7694.7 1720.44  7802.0 1718.67  7890.9 1720.51
#Mann=8,-1,0
  2822.7    0.05       0  5009.7    0.05       0  5029.7    0.05       0
  6888.0     0.1       0  7291.3    0.05       0  7343.8   0.075       0
  7392.2     0.1       0  7694.7    0.05       0
Bank Sta=5009.7,5029.7
Exp/Cntr=0.3,0.1

Type RM Length L Ch R = 1,11500,400,400,400
BEGIN DESCRIPTION:
Little Elm Creek 11500
END DESCRIPTION:
XS GIS Cut Line= 3
      1564830.00      6849263.00      1566239.70      6849292.35
      1568901.64      6849309.65
#Sta/Elev= 30
  3590.0 1725.11  3678.3 1723.23  4165.1 1714.66  4525.2 1713.55  4825.3 1710.74
  4885.3 1707.01  4985.3 1707.04  4995.3 1701.83  4995.8 1700.83  5014.8 1700.83
  5015.3 1701.83  5025.3 1706.88  5055.3 1708.98  5085.3 1714.39  5105.3 1712.82
  5175.3 1712.28  5275.3 1713.84  5405.3 1711.53  5953.7 1713.54  6132.4 1713.82
  6345.3 1713.22  6406.6 1714.44  6802.5 1715.32  6981.4 1716.66  7020.2 1717.15
  7198.5 1718.79  7297.4 1719.63  7396.4 1720.09  7495.4 1719.97  7662.0 1720.20
#Mann=14,-1,0
  3590.0   0.075       0  3678.3    0.05       0  4995.3    0.03       0
  5015.3    0.05       0  5953.7   0.075       0  6132.4    0.05       0
  6406.6     0.1       0  6802.5    0.05       0  6981.4   0.075       0
  7020.2    0.05       0  7198.5   0.075       0  7297.4     0.1       0
  7396.4   0.075       0  7495.4    0.05       0
Bank Sta=4995.3,5015.3
Exp/Cntr=0.3,0.1

Type RM Length L Ch R = 1,11100,320,320,320
BEGIN DESCRIPTION:
Mapping XS 1102e6e3
END DESCRIPTION:
XS GIS Cut Line= 3
      1564719.31      6849700.29      1566273.15      6849691.61
      1568581.12      6849674.26
#Sta/Elev= 30
  3461.7 1726.92  3497.4 1724.21  3515.3 1724.92  3637.4 1724.23  3667.4 1719.26
  3707.4 1721.62  3744.2 1720.66  3887.4 1717.63  4527.4 1712.17  4567.4 1710.72
  4587.4 1706.85  4667.4 1710.05  4897.4 1709.73  4977.4 1704.68  4987.4 1699.27
  4987.9 1698.27  5007.4 1699.27  5014.0 1704.28  5037.4 1703.69  5067.4 1711.13
  5111.9 1711.36  5258.8 1709.83  5817.4 1710.38  5877.4 1712.22  6180.1 1712.74
  6873.2 1715.44  6977.5 1715.23  7087.5 1718.67  7170.3 1717.83  7323.6 1719.19
#Mann=10,-1,0
  3461.7    0.05       0  3515.3   0.075       0  3744.2    0.05       0
  4987.4    0.03       0  5007.4    0.05       0  5111.9   0.075       0
  5258.8    0.05       0  6180.1     0.1       0  6873.2    0.05       0
  7170.3     0.1       0
Bank Sta=4987.4,5007.4
Exp/Cntr=0.3,0.1

Type RM Length L Ch R = 1,10780,716,716,716
BEGIN DESCRIPTION:
Little Elm Creek 10000
END DESCRIPTION:
XS GIS Cut Line= 3
      1564904.96      6850138.00      1566284.43      6850010.19
      1568816.59      6849795.77
#Sta/Elev= 30
  3627.2 1734.06  3672.5 1733.75  3687.5 1732.61  3757.8 1716.46  3791.4 1712.24
  4049.0 1715.32  4470.8 1709.86  4832.4 1709.91  4912.7 1708.31  4932.8 1704.24
  4962.9 1704.79  4970.0 1698.47  4970.5 1697.47  4990.0 1698.47  4993.1 1703.09
  5003.1 1704.67  5033.2 1703.85  5063.3 1709.38  5133.6 1708.86  5173.7 1710.96
  5193.8 1709.73  5451.5 1709.90  5585.2 1713.07  5695.6 1711.10  5886.3 1710.84
  6353.3 1712.80  6397.3 1715.41  6709.2 1716.46  6809.6 1714.64  7553.8 1719.47
#Mann=5,-1,0
  3627.2   0.075       0  3672.5    0.05       0  4970.0    0.03       0
  4990.0    0.05       0  6353.3     0.1       0
Bank Sta=4970,4990
Exp/Cntr=0.3,0.1

Type RM Length L Ch R = 1,10064,737,737,737
BEGIN DESCRIPTION:
Little Elm Creek 9500
END DESCRIPTION:
XS GIS Cut Line= 4
      1564971.09      6850846.12      1566325.23      6850724.60
      1567280.09      6850672.51      1569528.38      6850455.50
#Sta/Elev= 30
  3661.8 1715.05  3715.9 1715.53  3766.1 1710.53  3819.8 1710.10  3997.1 1709.29
  4167.7 1705.27  4212.9 1706.98  4304.4 1707.80  4931.6 1709.46  4991.0 1700.85
  4991.1 1698.63  4991.6 1697.63  5011.1 1698.63  5031.2 1702.37  5053.4 1702.41
  5081.2 1707.56  5141.3 1709.23  5712.2 1707.63  5822.3 1705.85  5862.4 1702.95
  5892.4 1707.24  6143.3 1709.18  6324.2 1712.74  6886.8 1713.74  6916.9 1715.65
  7803.7 1715.83  7812.2 1715.11  8055.7 1718.37  8102.9 1716.37  8236.4 1716.90
#Mann=9,-1,0
  3661.8   0.075       0  3819.8    0.05       0  4212.9    0.12       0
  4304.4    0.05       0  4991.1    0.05       0  5011.1    0.05       0
  7803.7     0.1       0  7812.2   0.075       0  8102.9    0.05       0
Bank Sta=4991.1,5011.1
Exp/Cntr=0.3,0.1

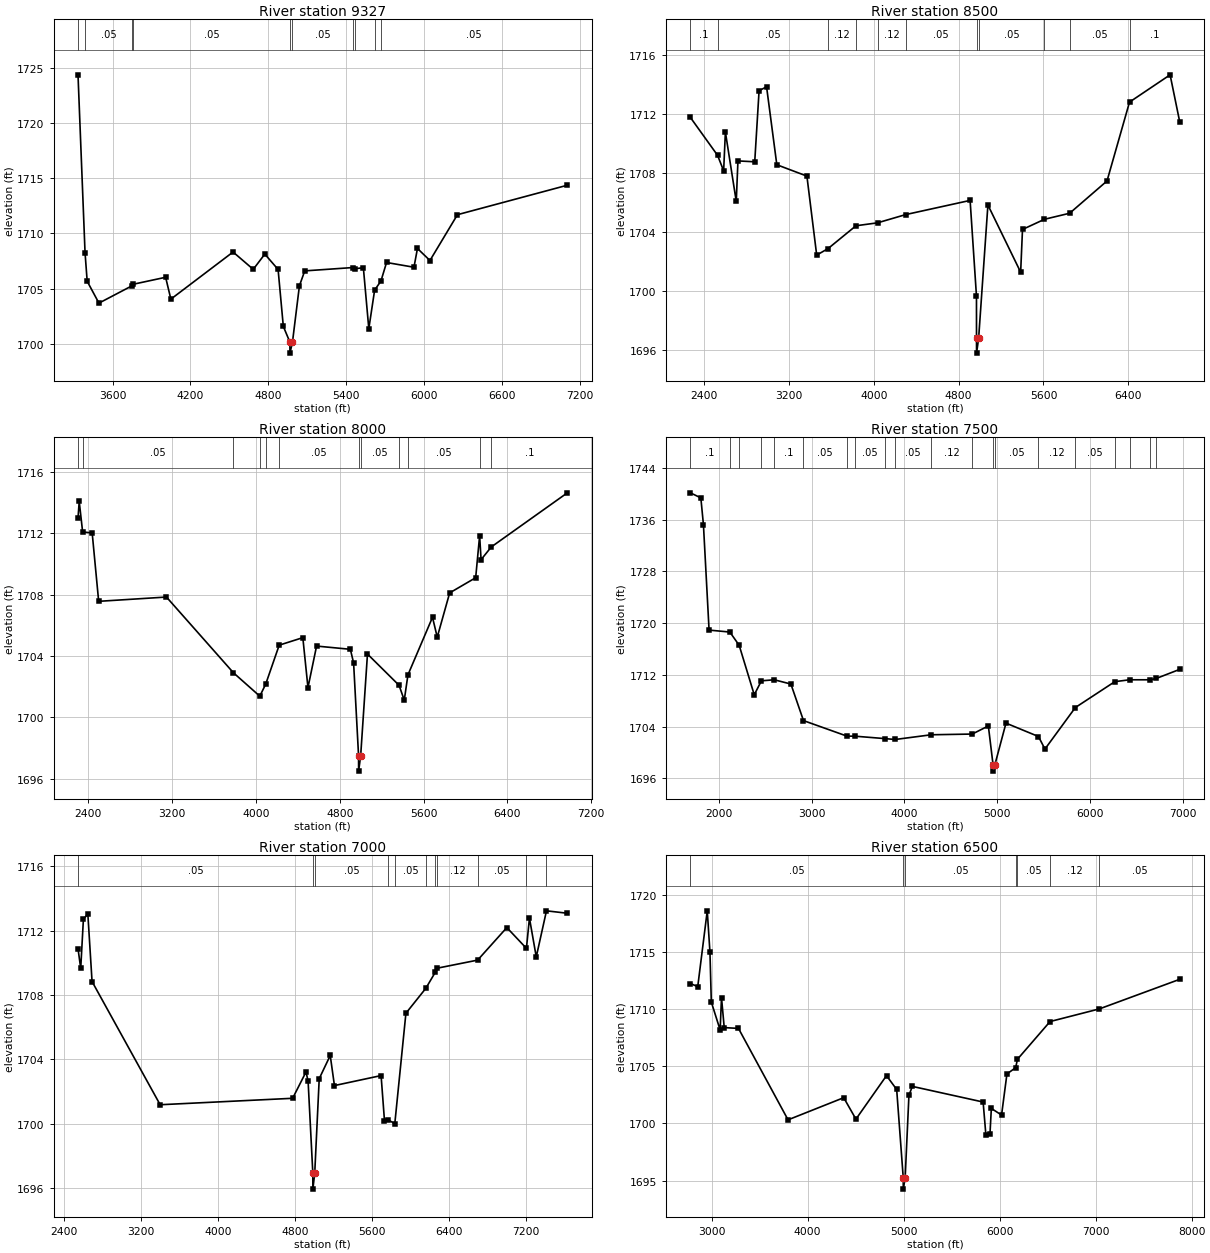
Type RM Length L Ch R = 1,9327,827,827,827
BEGIN DESCRIPTION:
Little Elm Creek 9000
END DESCRIPTION:
XS GIS Cut Line= 3
      1565054.95      6851538.01      1566697.62      6851337.23
      1568711.15      6850690.27
#Sta/Elev= 30
  3334.1 1724.37  3388.3 1708.26  3404.7 1705.67  3495.3 1703.69  3750.2 1705.26
  3755.8 1705.39  4009.1 1706.03  4049.4 1704.05  4528.6 1708.32  4684.1 1706.75
  4773.2 1708.13  4875.5 1706.74  4915.8 1701.58  4966.3 1700.16  4966.8 1699.16
  4986.3 1700.16  5039.8 1705.26  5080.8 1706.61  5448.9 1706.91  5466.7 1706.80
  5532.4 1706.90  5574.4 1701.37  5619.2 1704.87  5667.9 1705.69  5711.0 1707.37
  5922.2 1706.94  5949.1 1708.64  6045.4 1707.55  6257.2 1711.70  7103.9 1714.37
#Mann=10,-1,0
  3334.1   0.075       0  3388.3    0.05       0  3750.2    0.12       0
  3755.8    0.05       0  4966.3    0.05       0  4986.3    0.05       0
  5448.9    0.12       0  5466.7    0.05       0  5619.2    0.12       0
  5667.9    0.05       0
Bank Sta=4966.3,4986.3
Exp/Cntr=0.3,0.1

Type RM Length L Ch R = 1,8500,500,500,500
BEGIN DESCRIPTION:
Little Elm Creek 8500
END DESCRIPTION:
XS GIS Cut Line= 3
      1564432.89      6852651.67      1567095.83      6852052.10
      1568807.66      6851262.89
#Sta/Elev= 30
  2270.4 1711.75  2526.7 1709.18  2584.1 1708.13  2600.6 1710.76  2703.1 1706.05
  2719.0 1708.80  2877.3 1708.74  2918.3 1713.56  2988.9 1713.83  3085.6 1708.54
  3369.3 1707.77  3461.6 1702.41  3568.4 1702.85  3832.0 1704.40  4035.6 1704.60
  4301.6 1705.16  4908.4 1706.12  4968.4 1699.62  4968.7 1696.76  4969.2 1695.76
  4988.7 1696.76  5076.2 1705.81  5385.0 1701.25  5402.4 1704.15  5609.5 1704.84
  5847.2 1705.25  6199.4 1707.44  6411.5 1712.79  6794.3 1714.64  6885.0 1711.45
#Mann=11,-1,0
  2270.4     0.1       0  2526.7    0.05       0  3568.4    0.12       0
  3832.0    0.05       0  4035.6    0.12       0  4301.6    0.05       0
  4968.7    0.03       0  4988.7    0.05       0  5609.5    0.12       0
  5847.2    0.05       0  6411.5     0.1       0
Bank Sta=4968.7,4988.7
Exp/Cntr=0.3,0.1

Type RM Length L Ch R = 1,8000,500,500,500
BEGIN DESCRIPTION:
Little Elm Creek 8000
END DESCRIPTION:
XS GIS Cut Line= 3
      1564623.82      6853189.88      1567240.76      6852530.63
      1569016.20      6851670.78
#Sta/Elev= 30
  2301.3 1712.99  2312.8 1714.09  2345.4 1712.10  2436.6 1712.03  2498.5 1707.57
  3145.6 1707.85  3784.8 1702.91  4036.8 1701.38  4093.3 1702.17  4221.9 1704.71
  4447.5 1705.20  4496.5 1701.94  4578.7 1704.65  4901.2 1704.44  4932.2 1703.55
  4979.6 1697.49  4980.1 1696.49  4999.6 1697.49  5064.6 1704.13  5366.2 1702.09
  5415.8 1701.12  5450.9 1702.77  5685.4 1706.53  5730.6 1705.23  5849.2 1708.12
  6097.5 1709.11  6135.3 1711.85  6149.1 1710.29  6246.8 1711.12  6972.7 1714.65
#Mann=12,-1,0
  2301.3     0.1       0  2345.4    0.05       0  3784.8    0.12       0
  4036.8    0.05       0  4093.3    0.12       0  4221.9    0.05       0
  4979.6    0.05       0  4999.6    0.05       0  5366.2    0.12       0
  5450.9    0.05       0  6135.3   0.075       0  6246.8     0.1       0
Bank Sta=4979.6,4999.6
Exp/Cntr=0.3,0.1

Type RM Length L Ch R = 1,7500,500,500,500
BEGIN DESCRIPTION:
Little Elm Creek 7500
END DESCRIPTION:
XS GIS Cut Line= 3
      1564455.00      6854538.00      1567385.69      6853009.16
      1569041.16      6851949.25
#Sta/Elev= 30
  1694.5 1740.15  1807.3 1739.37  1835.3 1735.20  1895.9 1718.93  2119.6 1718.63
  2220.1 1716.58  2382.5 1708.93  2459.6 1711.09  2598.5 1711.25  2777.3 1710.59
  2912.9 1704.94  3381.4 1702.54  3469.0 1702.53  3787.5 1702.16  3900.2 1702.02
  4289.1 1702.75  4730.3 1702.86  4904.3 1704.11  4954.9 1698.13  4955.4 1697.13
  4974.9 1698.13  5094.2 1704.55  5444.1 1702.48  5513.9 1700.54  5841.4 1706.96
  6266.6 1710.96  6425.7 1711.25  6650.7 1711.25  6712.0 1711.45  6965.7 1712.86
#Mann=20,-1,0
  1694.5     0.1       0  2119.6   0.075       0  2220.1    0.05       0
  2459.6   0.075       0  2598.5     0.1       0  2912.9    0.05       0
  3381.4    0.12       0  3469.0    0.05       0  3787.5    0.12       0
  3900.2    0.05       0  4289.1    0.12       0  4730.3    0.05       0
  4954.9    0.03       0  4974.9    0.05       0  5444.1    0.12       0
  5841.4    0.05       0  6266.6    0.05       0  6425.7    0.05       0
  6650.7   0.075       0  6712.0     0.1       0
Bank Sta=4954.9,4974.9
Exp/Cntr=0.3,0.1

Type RM Length L Ch R = 1,7000,500,500,500
BEGIN DESCRIPTION:
Little Elm Creek 7000
END DESCRIPTION:
XS GIS Cut Line= 3
      1565396.43      6854717.64      1567525.06      6853489.32
      1569623.81      6851905.17
#Sta/Elev= 30
  2542.4 1710.88  2570.6 1709.66  2598.5 1712.71  2644.7 1713.03  2688.4 1708.84
  3396.4 1701.19  4773.7 1701.59  4913.0 1703.23  4934.5 1702.64  4983.4 1696.95
  4983.9 1695.95  5003.4 1696.95  5050.0 1702.81  5164.5 1704.25  5208.2 1702.38
  5693.2 1703.00  5728.6 1700.18  5765.1 1700.26  5835.6 1700.01  5951.2 1706.87
  6158.4 1708.42  6258.0 1709.43  6278.0 1709.67  6696.8 1710.17  7000.3 1712.19
  7204.1 1710.90  7235.5 1712.78  7306.3 1710.37  7412.4 1713.23  7629.5 1713.08
#Mann=11,-1,0
  2542.4    0.05       0  4983.4    0.05       0  5003.4    0.05       0
  5765.1    0.12       0  5835.6    0.05       0  6158.4    0.12       0
  6258.0    0.05       0  6278.0    0.12       0  6696.8    0.05       0
  7204.1   0.075       0  7412.4    0.05       0
Bank Sta=4983.4,5003.4
Exp/Cntr=0.3,0.1

Type RM Length L Ch R = 1,6500,1000,1000,1000
BEGIN DESCRIPTION:
Little Elm Creek 6500
END DESCRIPTION:
XS GIS Cut Line= 3
      1566082.18      6855533.62      1567659.31      6853970.95
      1569840.42      6852096.50
#Sta/Elev= 30
  2779.8 1712.26  2856.5 1711.99  2955.5 1718.63  2983.7 1715.00  2997.9 1710.64
  3089.8 1708.19  3104.0 1711.02  3132.3 1708.40  3280.7 1708.33  3797.0 1700.32
  4376.8 1702.26  4504.0 1700.38  4822.3 1704.19  4928.3 1702.98  4996.6 1695.25
  4997.1 1694.25  5016.6 1695.25  5055.9 1702.46  5091.1 1703.25  5828.5 1701.88
  5857.0 1699.03  5899.8 1699.07  5914.1 1701.32  6020.5 1700.74  6076.5 1704.34
  6167.2 1704.89  6186.2 1705.63  6525.5 1708.93  7039.8 1710.04  7875.9 1712.63
#Mann=7,-1,0
  2779.8    0.05       0  4996.6    0.05       0  5016.6    0.05       0
  6167.2    0.12       0  6186.2    0.05       0  6525.5    0.12       0
  7039.8    0.05       0
Bank Sta=4996.6,5016.6
Exp/Cntr=0.3,0.1