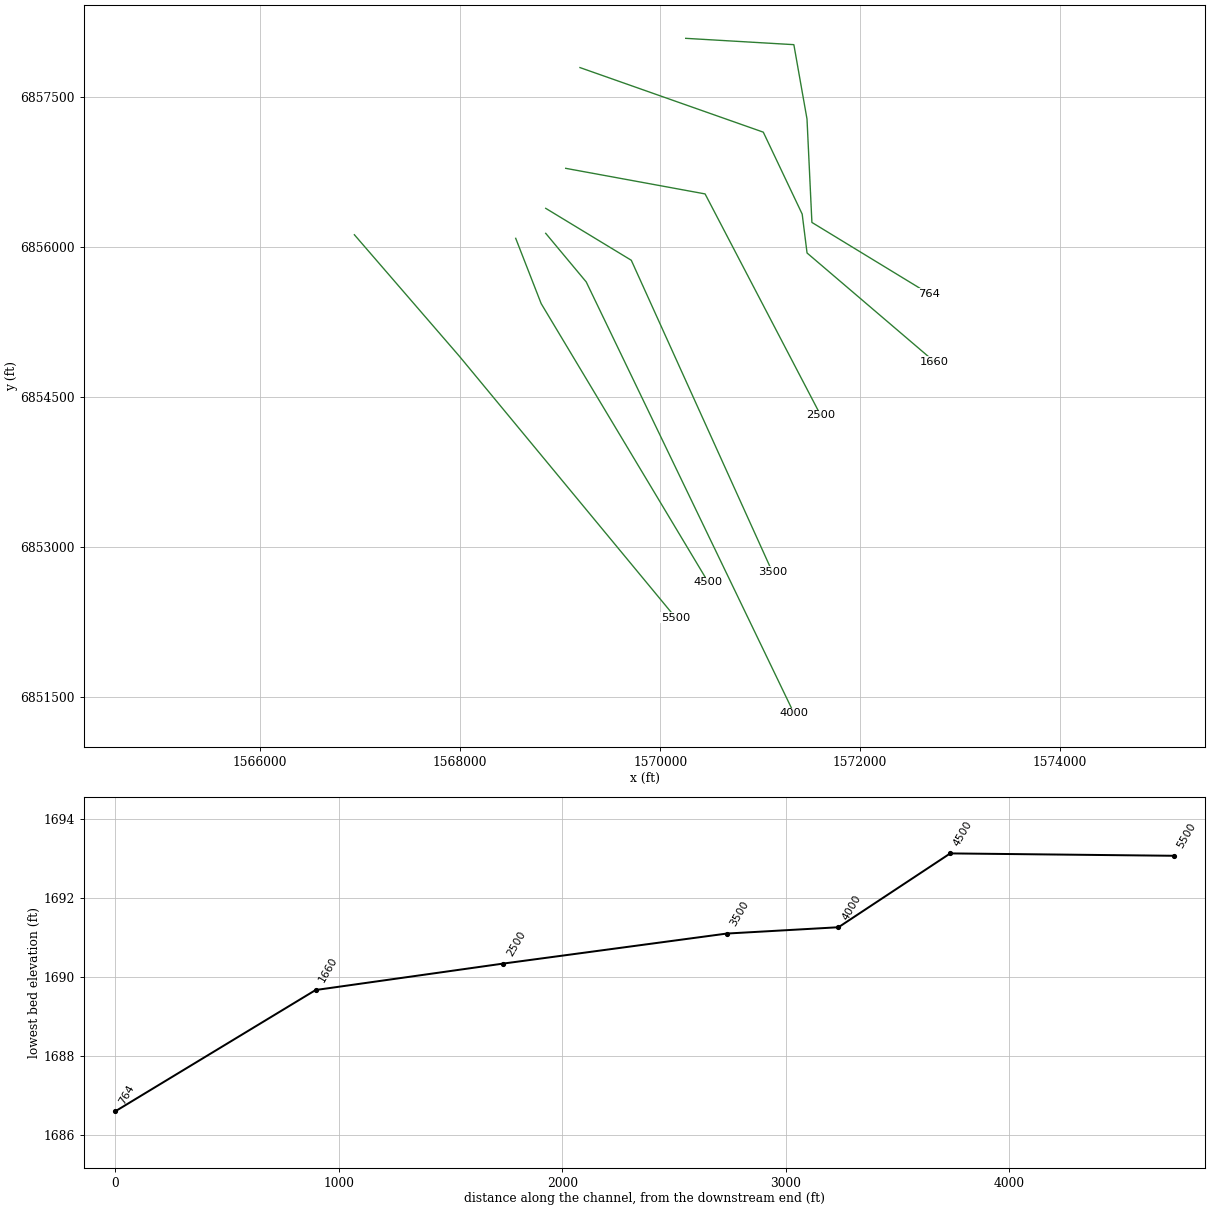
HEC-RAS study Little Elm Creek.prj: Little Elm Creek Base Level Engineering

--- Little Elm Creek.g01 (geometry) --- (continued)

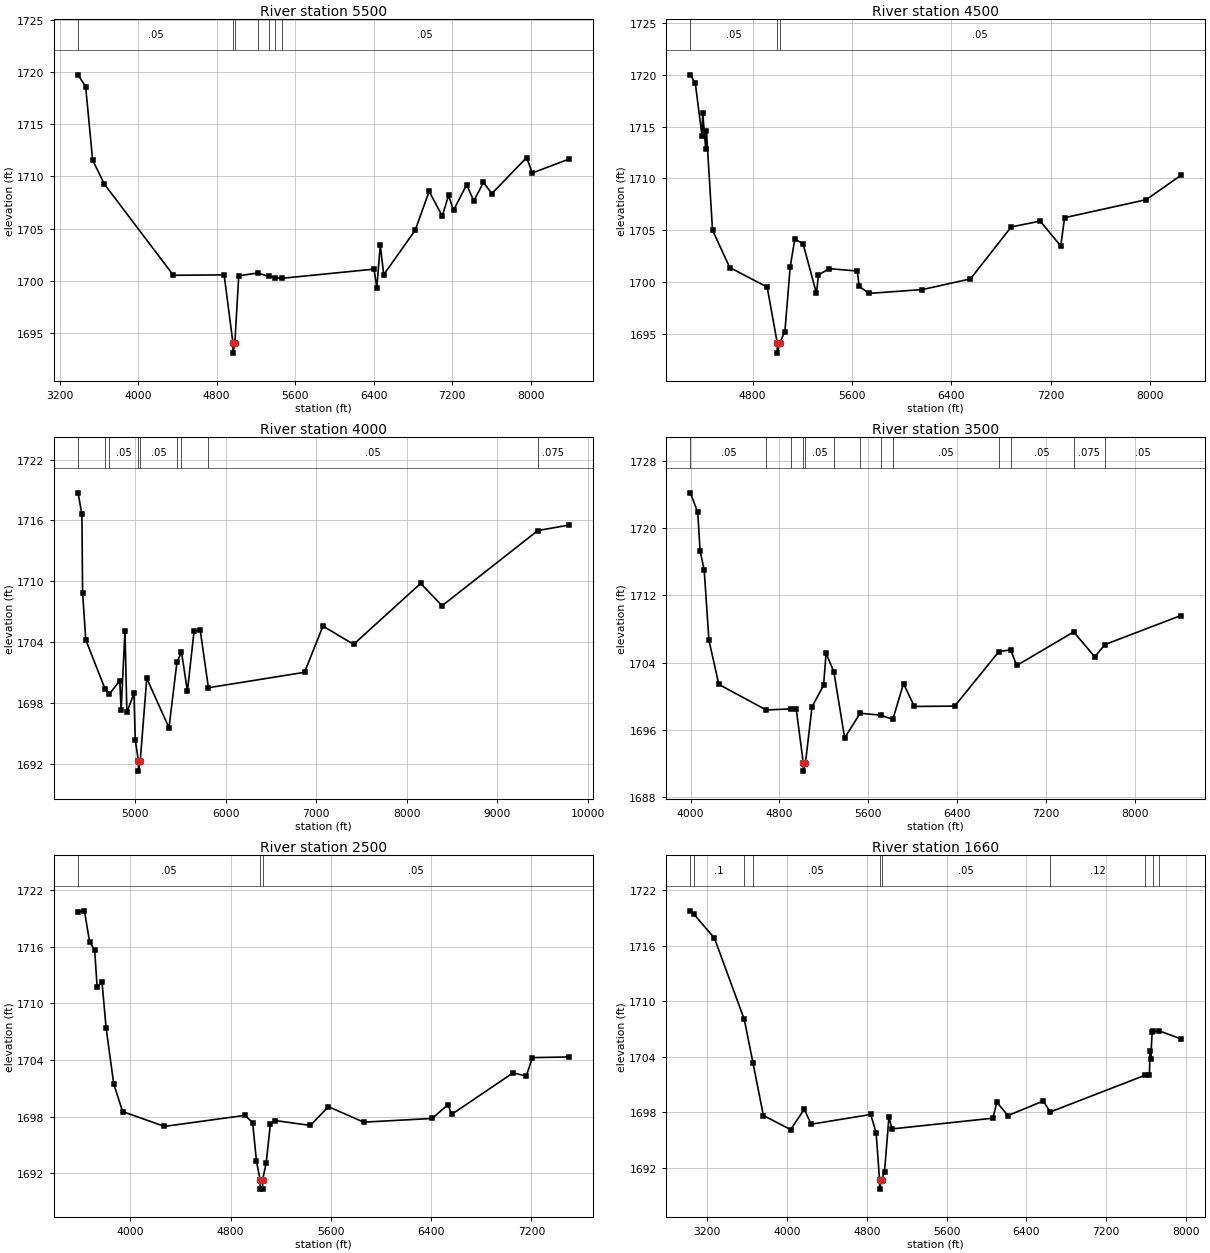
Type RM Length L Ch R = 1,5500,1000,1000,1000
BEGIN DESCRIPTION:
Little Elm Creek 5500
END DESCRIPTION:
XS GIS Cut Line= 3
      1566941.52      6856123.93      1567995.65      6854904.22
      1570153.34      6852295.79
#Sta/Elev= 30
  3387.9 1719.74  3465.2 1718.60  3536.5 1711.56  3657.2 1709.25  4359.2 1700.53
  4876.1 1700.57  4965.6 1694.07  4966.1 1693.07  4985.6 1694.07  5025.0 1700.48
  5218.7 1700.75  5333.6 1700.42  5399.4 1700.30  5463.5 1700.24  6403.2 1701.12
  6431.8 1699.35  6467.0 1703.41  6502.2 1700.59  6822.6 1704.84  6964.6 1708.57
  7098.7 1706.21  7162.6 1708.19  7213.4 1706.76  7347.5 1709.22  7419.2 1707.65
  7518.2 1709.43  7603.7 1708.36  7958.4 1711.81  8015.8 1710.33  8385.2 1711.65
#Mann=7,-1,0
  3387.9    0.05       0  4965.6    0.05       0  4985.6    0.05       0
  5218.7    0.12       0  5333.6    0.05       0  5399.4    0.12       0
  5463.5    0.05       0
Bank Sta=4965.6,4985.6
Exp/Cntr=0.3,0.1

Type RM Length L Ch R = 1,4500,500,500,500
BEGIN DESCRIPTION:
Little Elm Creek 4500
END DESCRIPTION:
XS GIS Cut Line= 3
      1568555.00      6856088.00      1568809.52      6855435.38
      1570480.79      6852648.02
#Sta/Elev= 30
  4299.5 1720.01  4338.9 1719.19  4393.3 1714.09  4398.6 1716.29  4423.1 1712.82
  4428.5 1714.61  4477.5 1705.01  4616.1 1701.40  4917.7 1699.51  4998.6 1694.13
  4999.1 1693.13  5018.6 1694.13  5060.2 1695.19  5102.9 1701.42  5139.9 1704.14
  5206.8 1703.70  5314.8 1698.90  5330.4 1700.67  5416.7 1701.29  5643.4 1701.06
  5658.9 1699.57  5738.6 1698.90  6168.2 1699.27  6555.1 1700.30  6883.6 1705.32
  7116.9 1705.88  7282.3 1703.48  7313.2 1706.21  7970.2 1707.95  8250.0 1710.30
#Mann=3,-1,0
  4299.5    0.05       0  4998.6    0.03       0  5018.6    0.05       0
Bank Sta=4998.6,5018.6
Exp/Cntr=0.3,0.1

Type RM Length L Ch R = 1,4000,500,500,500
BEGIN DESCRIPTION:
Little Elm Creek 4000
END DESCRIPTION:
XS GIS Cut Line= 3
      1568855.01      6856137.99      1569260.15      6855652.02
      1571338.09      6851337.42
#Sta/Elev= 30
  4367.3 1718.72  4409.6 1716.59  4417.4 1708.88  4452.5 1704.22  4663.7 1699.41
  4714.1 1698.87  4828.7 1700.19  4843.0 1697.25  4886.0 1705.10  4906.8 1697.07
  4984.9 1698.93  4999.2 1694.37  5034.5 1692.26  5035.0 1691.26  5054.5 1692.26
  5126.6 1700.42  5372.3 1695.54  5459.9 1701.98  5510.6 1703.02  5575.9 1699.14
  5649.4 1705.07  5717.2 1705.19  5808.0 1699.49  6870.6 1701.01  7074.2 1705.57
  7413.0 1703.77  8154.1 1709.78  8391.4 1707.58  9449.8 1715.00  9788.9 1715.53
#Mann=9,-1,0
  4367.3    0.05       0  4663.7    0.12       0  4714.1    0.05       0
  5034.5    0.05       0  5054.5    0.05       0  5459.9     0.1       0
  5510.6   0.075       0  5808.0    0.05       0  9449.8   0.075       0
Bank Sta=5034.5,5054.5
Exp/Cntr=0.3,0.1

Type RM Length L Ch R = 1,3500,1000,1000,1000
BEGIN DESCRIPTION:
Little Elm Creek 3500
END DESCRIPTION:
XS GIS Cut Line= 3
      1568855.03      6856387.98      1569710.78      6855868.66
      1571119.84      6852755.83
#Sta/Elev= 30
  3999.0 1724.19  4064.9 1721.87  4086.2 1717.28  4123.0 1715.03  4165.7 1706.68
  4254.8 1701.41  4682.2 1698.37  4900.6 1698.50  4952.7 1698.43  5015.3 1692.10
  5015.8 1691.10  5035.3 1692.10  5094.6 1698.77  5198.3 1701.30  5221.1 1705.11
  5291.2 1702.90  5388.3 1695.05  5527.5 1697.98  5715.9 1697.75  5822.1 1697.25
  5918.4 1701.50  6016.3 1698.79  6379.3 1698.83  6777.7 1705.32  6883.8 1705.51
  6938.1 1703.66  7451.3 1707.65  7641.0 1704.69  7733.2 1706.15  8416.9 1709.60
#Mann=13,-1,0
  3999.0    0.05       0  4682.2    0.12       0  4900.6    0.05       0
  5015.3    0.05       0  5035.3    0.05       0  5291.2     0.1       0
  5527.5    0.05       0  5715.9   0.075       0  5822.1    0.05       0
  6777.7   0.075       0  6883.8    0.05       0  7451.3   0.075       0
  7733.2    0.05       0
Bank Sta=5015.3,5035.3
Exp/Cntr=0.3,0.1

Type RM Length L Ch R = 1,2500,840,840,840
BEGIN DESCRIPTION:
Little Elm Creek 2500
END DESCRIPTION:
XS GIS Cut Line= 3
      1569054.96      6856788.01      1570448.68      6856532.22
      1571604.10      6854319.41
#Sta/Elev= 30
  3583.0 1719.67  3633.9 1719.80  3674.5 1716.55  3715.2 1715.65  3735.5 1711.69
  3774.0 1712.28  3806.7 1707.40  3867.7 1701.47  3938.5 1698.55  4272.4 1696.98
  4914.9 1698.15  4975.9 1697.37  5006.6 1693.28  5035.2 1691.34  5035.7 1690.34
  5054.7 1690.34  5055.2 1691.34  5083.7 1693.08  5117.6 1697.25  5155.6 1697.60
  5437.0 1697.08  5580.1 1699.07  5861.8 1697.43  6408.2 1697.82  6535.1 1699.29
  6562.8 1698.24  7053.8 1702.65  7158.6 1702.31  7208.4 1704.26  7496.3 1704.33
#Mann=3,-1,0
  3583.0    0.05       0  5035.2    0.03       0  5055.2    0.05       0
Bank Sta=5035.2,5055.2
Exp/Cntr=0.3,0.1

Type RM Length L Ch R = 1,1660,896,896,896
BEGIN DESCRIPTION:
Mapping XS 604eeb58
END DESCRIPTION:
XS GIS Cut Line= 5
      1569197.63      6857795.56      1571030.96      6857149.73
      1571419.85      6856330.28      1571468.46      6855941.39
      1572745.15      6854852.04
#Sta/Elev= 30
  3030.2 1719.76  3067.4 1719.37  3271.3 1716.80  3570.5 1708.02  3658.0 1703.32
  3762.3 1697.63  4035.5 1696.11  4172.5 1698.30  4241.6 1696.69  4839.4 1697.74
  4893.4 1695.77  4927.6 1690.67  4928.1 1689.67  4947.6 1690.67  4977.7 1691.57
  5022.0 1697.45  5053.4 1696.18  6064.7 1697.34  6105.0 1699.06  6215.9 1697.62
  6570.7 1699.20  6640.0 1698.01  7588.4 1701.97  7635.3 1702.02  7641.8 1704.59
  7648.7 1703.70  7662.7 1706.70  7674.2 1706.73  7734.6 1706.78  7951.2 1705.92
#Mann=10,-1,0
  3030.2   0.075       0  3067.4     0.1       0  3570.5   0.075       0
  3658.0    0.05       0  4927.6    0.05       0  4947.6    0.05       0
  6640.0    0.12       0  7588.4   0.075       0  7674.2    0.05       0
  7734.6   0.075       0
Bank Sta=4927.6,4947.6
Exp/Cntr=0.3,0.1

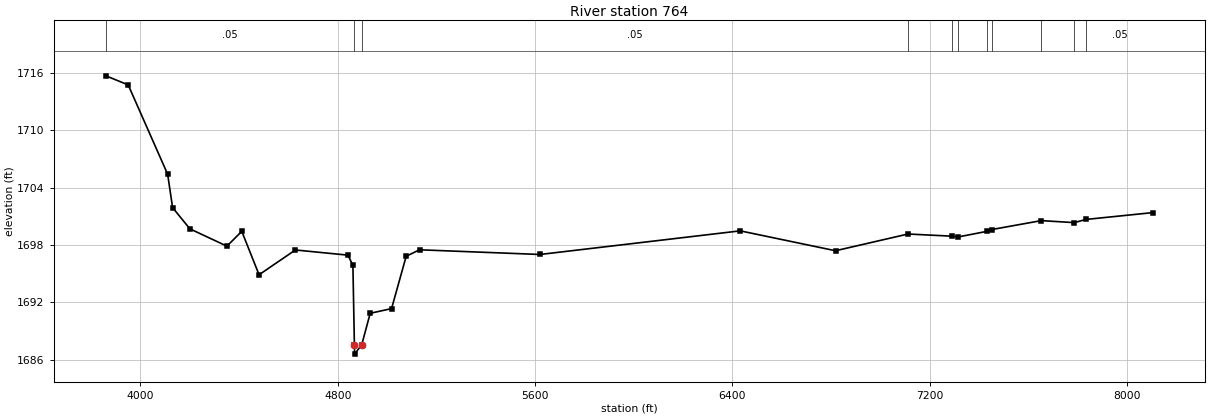
Type RM Length L Ch R = 1,764,0,0,0
BEGIN DESCRIPTION:
Little Elm Creek 1500
END DESCRIPTION:
XS GIS Cut Line= 5
      1570254.99      6858088.00      1571336.51      6858024.73
      1571467.95      6857281.58      1571517.07      6856246.95
      1572689.27      6855532.53
#Sta/Elev= 30
  3860.0 1715.70  3950.4 1714.75  4110.4 1705.41  4130.5 1701.92  4200.6 1699.70
  4350.8 1697.89  4411.0 1699.44  4481.1 1694.90  4628.4 1697.49  4841.7 1696.95
  4861.7 1695.87  4867.7 1687.60  4868.5 1686.60  4897.7 1687.60  4931.8 1690.87
  5018.5 1691.36  5077.7 1696.83  5131.8 1697.51  5620.4 1697.02  6432.5 1699.49
  6818.8 1697.41  7113.0 1699.16  7293.1 1698.93  7315.6 1698.85  7433.6 1699.44
  7453.2 1699.63  7653.4 1700.56  7787.4 1700.35  7833.5 1700.68  8106.6 1701.40
#Mann=11,-1,0
  3860.0    0.05       0  4867.7    0.05       0  4897.7    0.05       0
  7113.0    0.12       0  7293.1    0.05       0  7315.6    0.12       0
  7433.6    0.05       0  7453.2    0.12       0  7653.4    0.05       0
  7787.4    0.12       0  7833.5    0.05       0
Bank Sta=4867.7,4897.7
Exp/Cntr=0.3,0.1

Chan Stop Cuts=-1