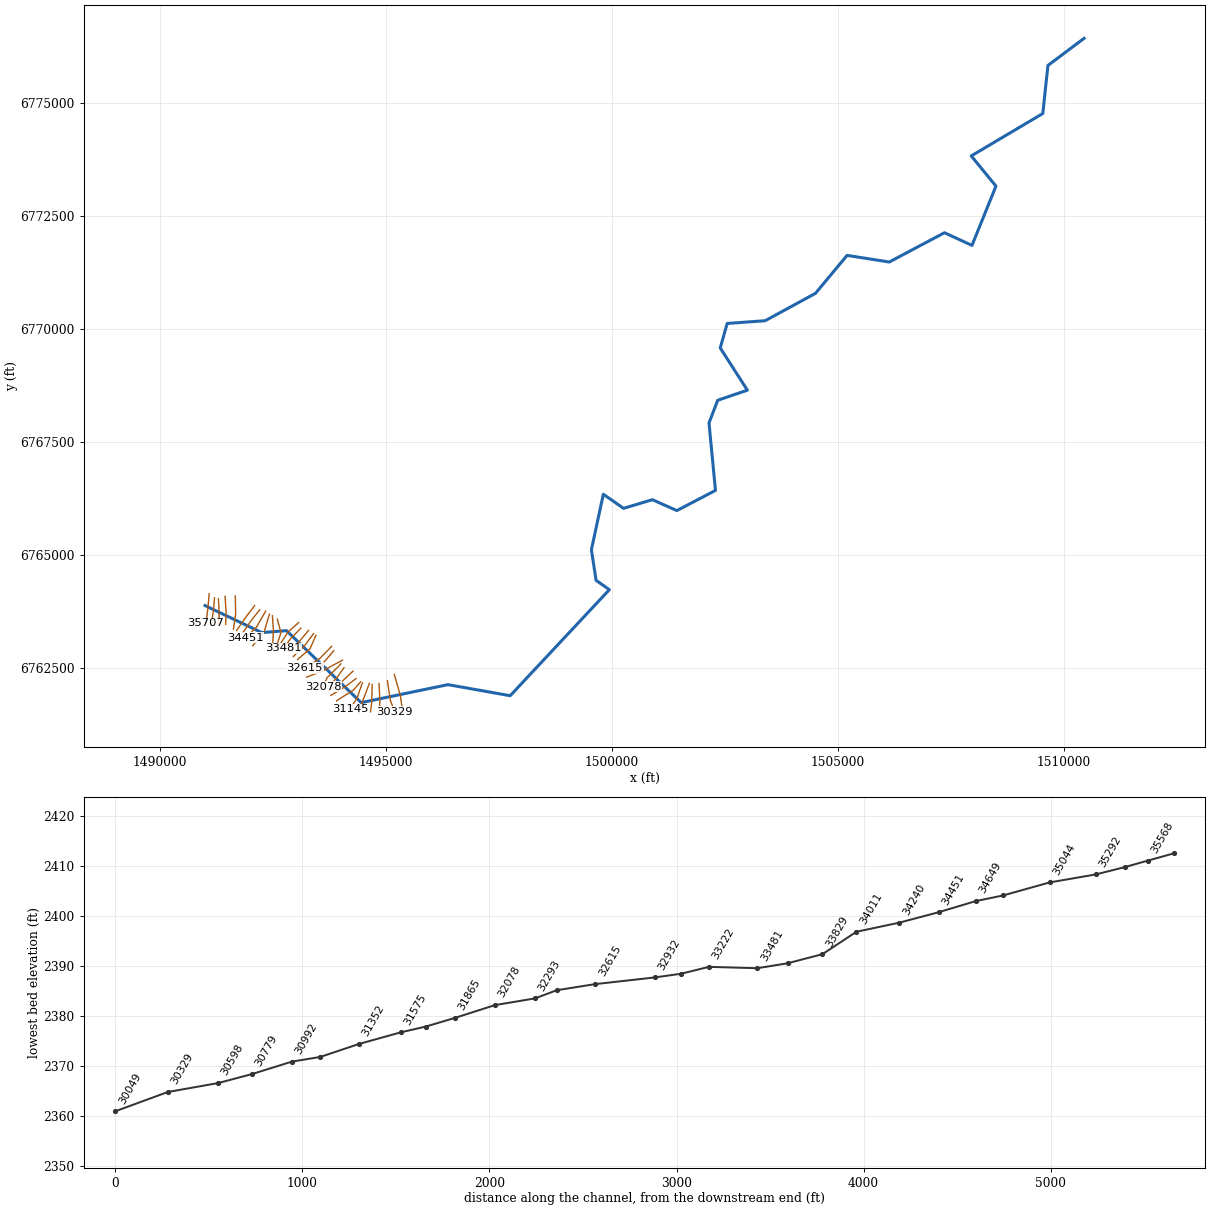
--- Little Elm Creek 2.prj (project) ---

Proj Title=Little Elm Creek 2 Base Level Engineering
Current Plan=p01
Default Exp/Contr=0.3,0.1
English Units
Geom File=g01
Flow File=f01
Plan File=p01
BEGIN DESCRIPTION:
Little Elm Creek 2
END DESCRIPTION:

--- Little Elm Creek 2.p01 (plan) ---

Plan Title=Multiple Run
Short Identifier=Multiple
Geom File=g01
Flow File=f01
Subcritical Flow
K Sum by GR= 0
Std Step Tol= 0.01
Critical Tol= 0.01
Num of Std Step Trials= 20
Max Error Tol= 0.3
Flow Tol Ratio= 0.001
Split Flow NTrial= 30
Split Flow Tol= 0.02
Split Flow Ratio= 0.02
Log Output Level= 0
Friction Slope Method= 1
Unsteady Friction Slope Method= 2
Unsteady Bridges Friction Slope Method= 1
Parabolic Critical Depth
Global Vel Dist=  1 , 1 , 1
Global Log Level= 0
CheckData=True
Encroach Param= -1, 0, 0, 0
BEGIN DESCRIPTION:
Multiple Run
END DESCRIPTION:

--- Little Elm Creek 2.f01 (steady flow) ---

Flow Title=Multiple
Number of Profiles=7
Profile Names=10-year,25-year,50-year,1pct_min,100-year,1pct_plu,500-year
River Rch & RM= Little Elm Creek,Reach-1,35707
     194     261     314     234     376     517     543
River Rch & RM= Little Elm Creek,Reach-1,34795
     403     570     710     547     876    1210    1350
River Rch & RM= Little Elm Creek,Reach-1,27415
     562     813    1030     803    1290    1770    2040
River Rch & RM= Little Elm Creek,Reach-1,20096
     871    1290    1660    1310    2100    2890    3440
River Rch & RM= Little Elm Creek,Reach-1,18966
    1030    1530    1980    1580    2530    3480    4170
River Rch & RM= Little Elm Creek,Reach-1,18337
    1210    1830    2370    1900    3050    4200    5100
River Rch & RM= Little Elm Creek,Reach-1,13896
    1260    1890    2460    1980    3170    4360    5300
River Rch & RM= Little Elm Creek,Reach-1,12508
    1500    2280    2980    2400    3850    5300    6500
River Rch & RM= Little Elm Creek,Reach-1,10466
    1600    2440    3200    2580    4140    5700    7030
River Rch & RM= Little Elm Creek,Reach-1,8729
    1620    2470    3240    2620    4200    5780    7140
River Rch & RM= Little Elm Creek,Reach-1,8159
    1770    2690    3520    2840    4550    6270    7720
River Rch & RM= Little Elm Creek,Reach-1,1064
    1800    2750    3600    2910    4660    6410    7910
Boundary for River Rch & Prof#=Little Elm Creek,Reach-1,1
Up Type=0
Dn Type=3
Dn Slope=0.005
Boundary for River Rch & Prof#=Little Elm Creek,Reach-1,2
Up Type=0
Dn Type=3
Dn Slope=0.005
Boundary for River Rch & Prof#=Little Elm Creek,Reach-1,3
Up Type=0
Dn Type=3
Dn Slope=0.005
Boundary for River Rch & Prof#=Little Elm Creek,Reach-1,4
Up Type=0
Dn Type=3
Dn Slope=0.005
Boundary for River Rch & Prof#=Little Elm Creek,Reach-1,5
Up Type=0
Dn Type=3
Dn Slope=0.005
Boundary for River Rch & Prof#=Little Elm Creek,Reach-1,6
Up Type=0
Dn Type=3
Dn Slope=0.005
Boundary for River Rch & Prof#=Little Elm Creek,Reach-1,7
Up Type=0
Dn Type=3
Dn Slope=0.005

--- Little Elm Creek 2.g01 (geometry) ---

Geom Title=Existing Conditions

River Reach=Little Elm Creek,Reach-1
Reach XY= 30
      1491005.00      6763888.00      1492260.85      6763290.06
      1492807.31      6763332.91      1494460.84      6761740.05
      1496379.92      6762138.20      1497757.43      6761893.52
      1499951.54      6764239.50      1499657.91      6764445.91
      1499554.21      6765123.18      1499818.46      6766351.63
      1500265.44      6766038.82      1500905.00      6766230.44
      1501444.50      6765989.19      1502299.48      6766435.57
      1502156.23      6767927.49      1502348.61      6768430.00
      1503005.05      6768653.32      1502405.00      6769588.00
      1502558.15      6770129.68      1503399.17      6770190.06
      1504511.45      6770795.74      1505210.97      6771635.86
      1506144.60      6771488.96      1507365.51      6772136.79
      1507975.03      6771857.28      1508504.96      6773167.98
      1507958.53      6773836.53      1509541.40      6774774.76
      1509655.00      6775838.00      1510455.00      6776438.00

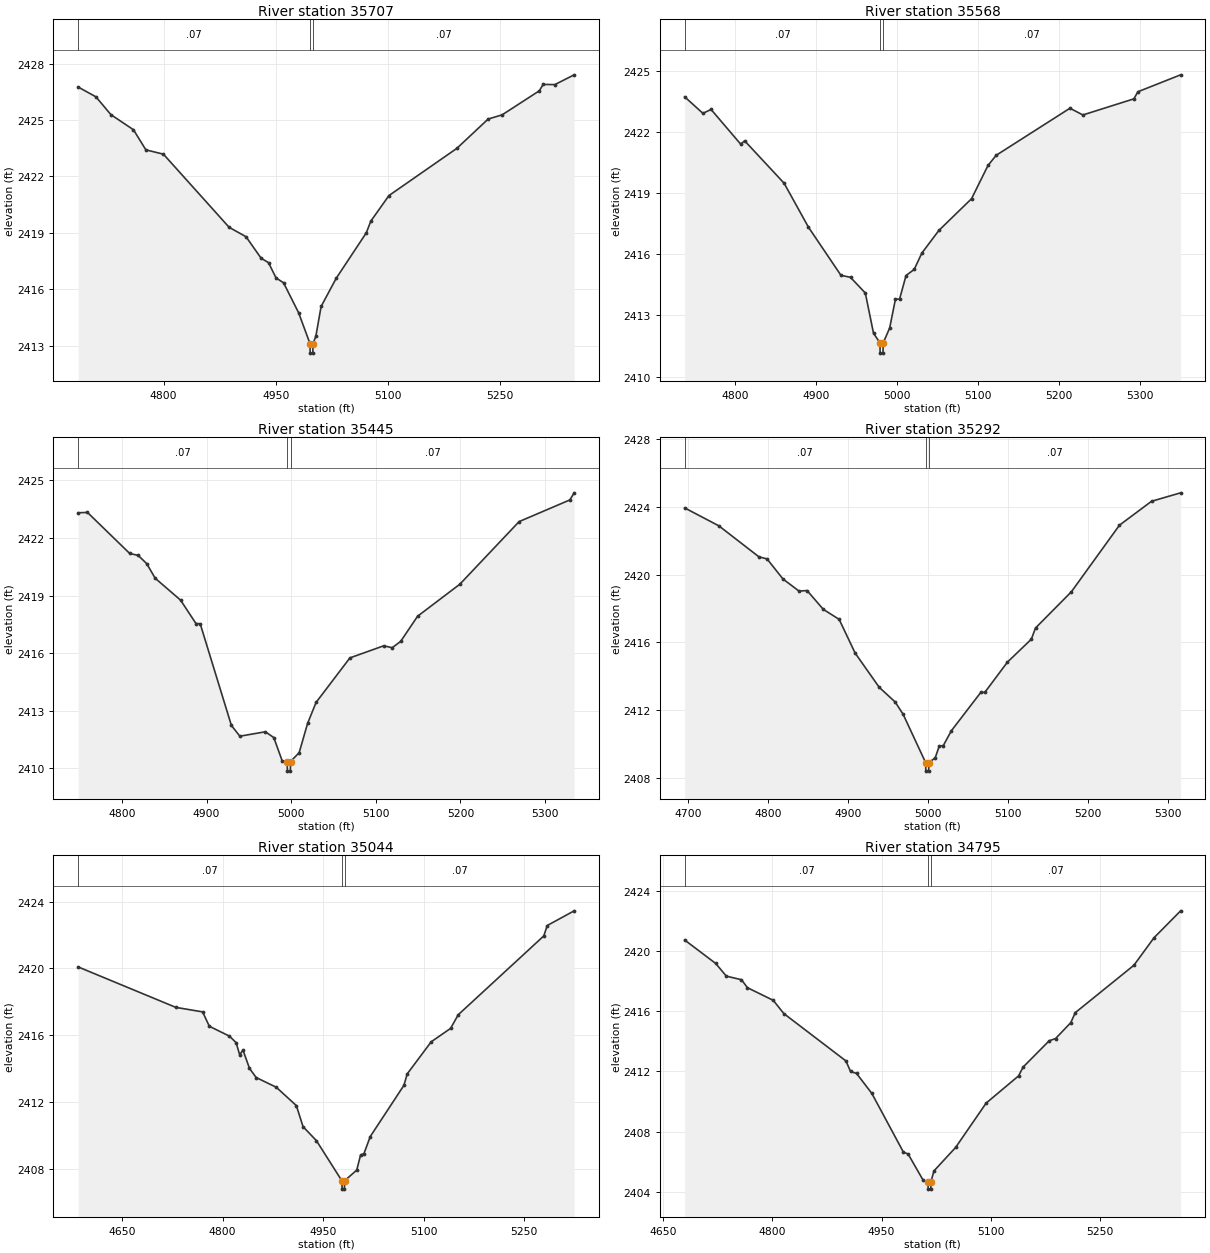
Type RM Length L Ch R = 1,35707,139,139,139
BEGIN DESCRIPTION:
Little Elm Creek 2 4607
END DESCRIPTION:
XS GIS Cut Line= 3
      1491098.19      6764151.58      1491070.22      6763838.53
      1491024.48      6763492.44
#Sta/Elev= 30
  4685.7 2426.75  4709.4 2426.23  4729.5 2425.28  4759.6 2424.48  4776.2 2423.41
  4799.7 2423.18  4887.6 2419.29  4910.2 2418.79  4930.3 2417.65  4940.3 2417.41
  4950.3 2416.60  4960.4 2416.34  4980.5 2414.75  4995.8 2413.10  4996.0 2412.60
  4999.5 2412.60  4999.8 2413.10  5003.6 2413.50  5010.6 2415.08  5030.8 2416.58
  5071.1 2419.00  5077.1 2419.62  5101.4 2420.98  5192.2 2423.49  5234.1 2425.05
  5252.7 2425.27  5302.5 2426.55  5307.6 2426.89  5323.3 2426.88  5349.1 2427.40
#Mann=3,-1,0
  4685.7    0.07       0  4995.8    0.07       0  4999.8    0.07       0
Bank Sta=4995.8,4999.8
Exp/Cntr=0.3,0.1

Type RM Length L Ch R = 1,35568,123,123,123
BEGIN DESCRIPTION:
Little Elm Creek 2 4606
END DESCRIPTION:
XS GIS Cut Line= 3
      1491215.38      6764060.48      1491195.35      6763798.85
      1491141.60      6763452.90
#Sta/Elev= 30
  4737.6 2423.73  4760.1 2422.92  4770.2 2423.11  4806.7 2421.41  4811.7 2421.57
  4860.4 2419.49  4890.5 2417.33  4930.6 2414.97  4942.4 2414.87  4960.7 2414.10
  4970.8 2412.13  4978.8 2411.65  4979.0 2411.15  4982.5 2411.15  4982.8 2411.65
  4990.8 2412.39  4997.9 2413.80  5003.0 2413.80  5011.0 2414.96  5021.1 2415.26
  5030.5 2416.06  5051.5 2417.17  5091.9 2418.73  5112.2 2420.36  5122.3 2420.86
  5213.4 2423.17  5229.4 2422.84  5292.3 2423.63  5297.4 2423.98  5350.1 2424.81
#Mann=3,-1,0
  4737.6    0.07       0  4978.8    0.07       0  4982.8    0.07       0
Bank Sta=4978.8,4982.8
Exp/Cntr=0.3,0.1

Type RM Length L Ch R = 1,35445,153,153,153
BEGIN DESCRIPTION:
Little Elm Creek 2 4605
END DESCRIPTION:
XS GIS Cut Line= 3
      1491302.18      6764038.83      1491316.01      6763787.41
      1491315.21      6763452.91
#Sta/Elev= 30
  4748.2 2423.31  4759.1 2423.33  4809.1 2421.19  4819.1 2421.09  4829.2 2420.66
  4839.2 2419.90  4869.2 2418.76  4887.4 2417.54  4892.4 2417.53  4929.3 2412.23
  4939.3 2411.67  4969.4 2411.90  4979.4 2411.60  4989.4 2410.38  4995.2 2410.35
  4995.5 2409.85  4999.0 2409.85  4999.2 2410.35  5009.4 2410.81  5019.4 2412.34
  5029.4 2413.43  5069.4 2415.75  5109.4 2416.38  5119.4 2416.28  5129.4 2416.61
  5149.4 2417.92  5199.4 2419.59  5269.4 2422.85  5329.4 2423.98  5334.5 2424.35
#Mann=3,-1,0
  4748.2    0.07       0  4995.2    0.07       0  4999.2    0.07       0
Bank Sta=4995.2,4999.2
Exp/Cntr=0.3,0.1

Type RM Length L Ch R = 1,35292,248,248,248
BEGIN DESCRIPTION:
Little Elm Creek 2 35292.401
END DESCRIPTION:
XS GIS Cut Line= 3
      1491448.74      6764090.72      1491473.59      6763719.39
      1491460.28      6763471.61
#Sta/Elev= 30
  4695.7 2423.94  4738.5 2422.88  4788.6 2421.05  4798.7 2420.93  4818.7 2419.74
  4838.7 2419.03  4848.8 2419.06  4869.1 2417.95  4888.9 2417.36  4908.9 2415.37
  4939.0 2413.35  4959.0 2412.48  4969.0 2411.75  4997.1 2408.90  4997.3 2408.40
  5000.8 2408.40  5001.1 2408.90  5009.1 2409.19  5014.1 2409.88  5019.2 2409.91
  5029.2 2410.78  5066.1 2413.05  5071.1 2413.05  5099.3 2414.83  5129.3 2416.19
  5134.5 2416.85  5179.4 2418.99  5239.5 2422.92  5279.6 2424.33  5316.0 2424.83
#Mann=3,-1,0
  4695.7    0.07       0  4997.1    0.07       0  5001.1    0.07       0
Bank Sta=4997.1,5001.1
Exp/Cntr=0.3,0.1

Type RM Length L Ch R = 1,35044,249,249,249
BEGIN DESCRIPTION:
Little Elm Creek 2 35043.78
END DESCRIPTION:
XS GIS Cut Line= 3
      1491675.30      6764103.76      1491683.11      6763702.75
      1491633.62      6763366.76
#Sta/Elev= 30
  4584.3 2420.09  4730.1 2417.67  4770.1 2417.40  4780.1 2416.54  4810.1 2415.95
  4820.1 2415.56  4825.4 2414.84  4830.4 2415.11  4840.1 2414.02  4850.1 2413.47
  4880.1 2412.89  4910.1 2411.79  4920.1 2410.53  4940.1 2409.69  4978.1 2407.29
  4978.4 2406.79  4981.9 2406.79  4982.1 2407.29  5000.3 2407.93  5006.0 2408.83
  5011.1 2408.92  5020.5 2409.94  5070.7 2413.00  5075.7 2413.69  5111.5 2415.61
  5140.4 2416.41  5151.9 2417.23  5279.7 2421.95  5284.8 2422.57  5325.0 2423.45
#Mann=3,-1,0
  4584.3    0.07       0  4978.1    0.07       0  4982.1    0.07       0
Bank Sta=4978.1,4982.1
Exp/Cntr=0.3,0.1

Type RM Length L Ch R = 1,34795,146,146,146
BEGIN DESCRIPTION:
Little Elm Creek 2 34794.6
END DESCRIPTION:
XS GIS Cut Line= 3
      1492104.99      6763887.99      1491910.36      6763633.86
      1491705.02      6763338.04
#Sta/Elev= 30
  4679.9 2420.74  4722.5 2419.18  4737.0 2418.34  4757.8 2418.10  4766.0 2417.57
  4801.4 2416.73  4815.9 2415.85  4901.1 2412.70  4907.4 2412.00  4915.6 2411.87
  4936.5 2410.55  4980.0 2406.63  4986.3 2406.52  5007.1 2404.76  5013.6 2404.68
  5013.9 2404.18  5017.5 2404.18  5017.7 2404.68  5021.8 2405.39  5051.5 2406.95
  5093.4 2409.90  5137.9 2411.71  5144.0 2412.29  5179.8 2414.04  5188.6 2414.19
  5209.5 2415.25  5215.6 2415.91  5296.0 2419.06  5323.6 2420.89  5360.1 2422.68
#Mann=3,-1,0
  4679.9    0.07       0  5013.6    0.07       0  5017.7    0.07       0
Bank Sta=5013.6,5017.7
Exp/Cntr=0.3,0.1

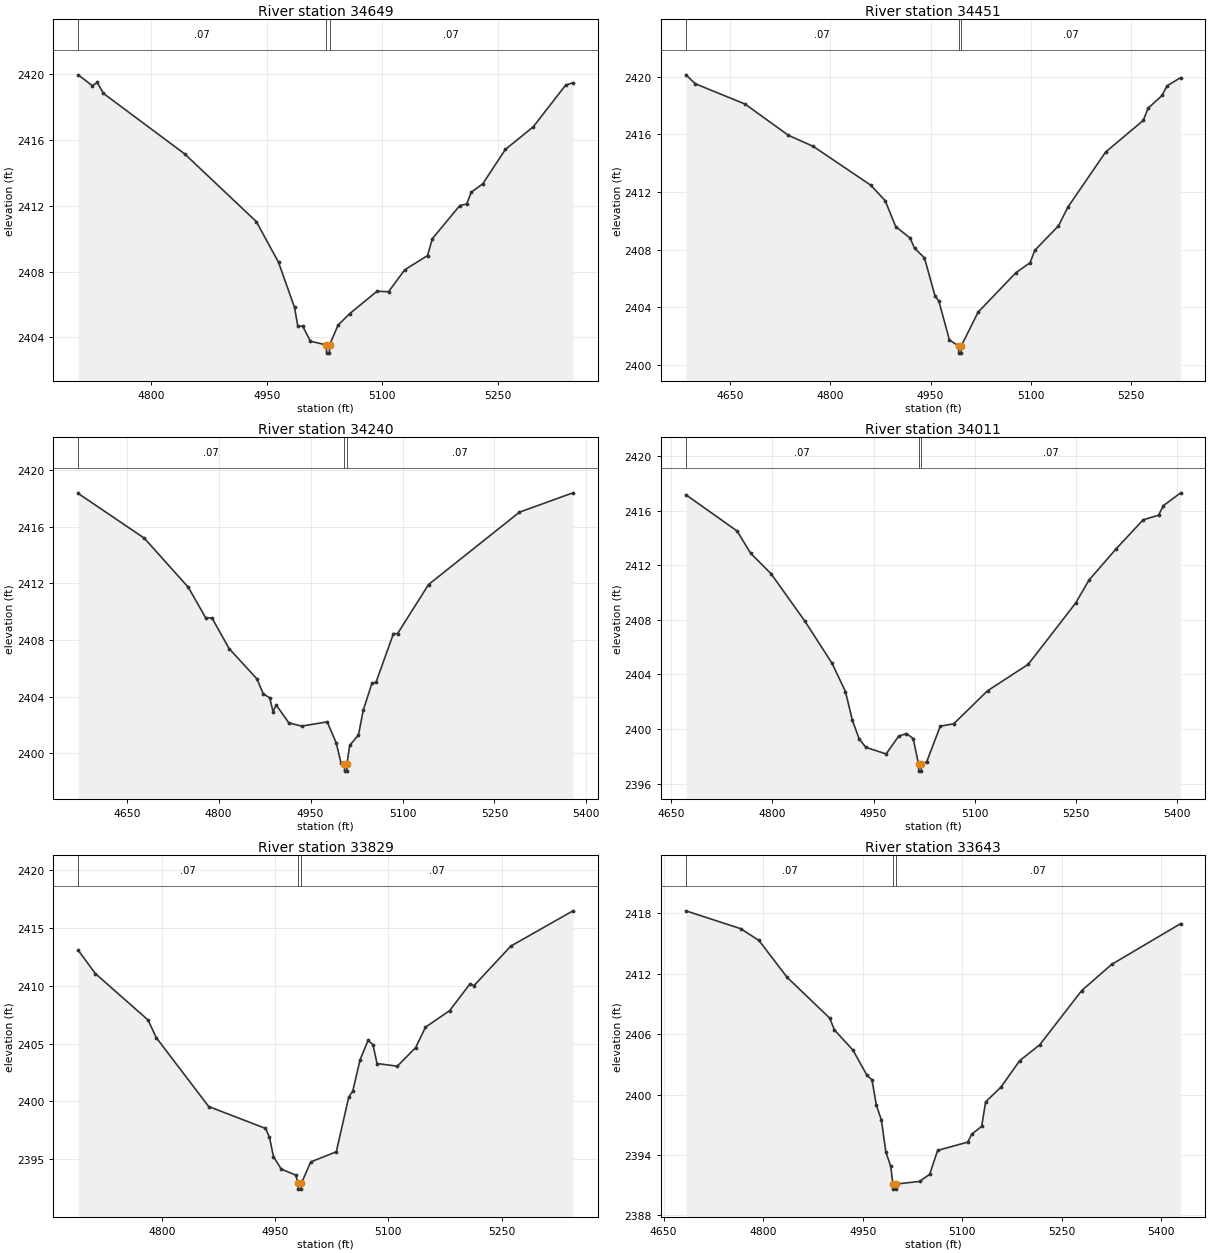
Type RM Length L Ch R = 1,34649,198,198,198
BEGIN DESCRIPTION:
Little Elm Creek 2 34649.14
END DESCRIPTION:
XS GIS Cut Line= 3
      1492214.33      6763793.86      1492034.67      6763567.33
      1491834.14      6763275.64
#Sta/Elev= 30
  4704.7 2419.96  4723.2 2419.30  4729.5 2419.50  4737.6 2418.83  4843.3 2415.15
  4936.3 2411.04  4965.1 2408.57  4985.9 2405.83  4990.2 2404.69  4996.5 2404.69
  5006.6 2403.77  5027.4 2403.55  5027.6 2403.05  5031.2 2403.05  5031.5 2403.55
  5042.5 2404.75  5057.4 2405.44  5093.2 2406.81  5108.1 2406.78  5129.1 2408.11
  5158.9 2408.98  5165.0 2410.00  5200.8 2412.02  5209.6 2412.11  5215.7 2412.83
  5230.6 2413.34  5260.0 2415.43  5296.2 2416.80  5338.2 2419.33  5347.8 2419.48
#Mann=3,-1,0
  4704.7    0.07       0  5027.4    0.07       0  5031.5    0.07       0
Bank Sta=5027.4,5031.5
Exp/Cntr=0.3,0.1

Type RM Length L Ch R = 1,34451,211,211,211
BEGIN DESCRIPTION:
Little Elm Creek 2 34451.43
END DESCRIPTION:
XS GIS Cut Line= 3
      1492347.16      6763765.23      1492138.84      6763403.27
      1491904.47      6763179.32
#Sta/Elev= 30
  4583.2 2420.12  4597.4 2419.50  4672.1 2418.09  4736.8 2415.93  4774.2 2415.16
  4860.4 2412.47  4882.0 2411.40  4897.8 2409.60  4919.3 2408.81  4926.1 2408.10
  4940.9 2407.43  4956.7 2404.80  4962.5 2404.43  4978.3 2401.74  4992.0 2401.33
  4992.3 2400.83  4995.9 2400.83  4996.1 2401.33  5021.3 2403.67  5077.9 2406.40
  5099.3 2407.10  5106.2 2407.95  5141.8 2409.65  5155.9 2410.95  5212.5 2414.77
  5268.9 2416.96  5276.1 2417.80  5297.1 2418.69  5304.4 2419.35  5325.0 2419.93
#Mann=3,-1,0
  4583.2    0.07       0  4992.0    0.07       0  4996.1    0.07       0
Bank Sta=4992,4996.1
Exp/Cntr=0.3,0.1

Type RM Length L Ch R = 1,34240,229,229,229
BEGIN DESCRIPTION:
Little Elm Creek 2 34239.61
END DESCRIPTION:
XS GIS Cut Line= 3
      1492430.51      6763697.54      1492310.71      6763293.89
      1492060.70      6762999.60
#Sta/Elev= 30
  4570.8 2418.35  4678.9 2415.18  4750.6 2411.71  4778.6 2409.58  4789.4 2409.53
  4817.0 2407.39  4862.4 2405.25  4872.8 2404.19  4883.3 2403.91  4888.7 2402.94
  4893.9 2403.40  4914.5 2402.14  4935.4 2401.91  4977.1 2402.21  4991.8 2400.72
  4999.6 2399.32  5005.2 2399.23  5005.5 2398.73  5009.1 2398.73  5009.3 2399.23
  5013.8 2400.55  5028.1 2401.28  5035.8 2403.02  5050.1 2404.94  5056.7 2405.00
  5085.2 2408.45  5091.8 2408.44  5142.4 2411.91  5290.6 2417.02  5378.0 2418.39
#Mann=3,-1,0
  4570.8    0.07       0  5005.2    0.07       0  5009.3    0.07       0
Bank Sta=5005.2,5009.3
Exp/Cntr=0.3,0.1

Type RM Length L Ch R = 1,34011,182,182,182
BEGIN DESCRIPTION:
Little Elm Creek 2 34010.95
END DESCRIPTION:
XS GIS Cut Line= 3
      1492495.61      6763663.68      1492519.05      6763345.98
      1492498.24      6762932.47
#Sta/Elev= 30
  4672.2 2417.16  4748.1 2414.50  4768.1 2412.87  4798.2 2411.38  4848.4 2407.90
  4888.5 2404.82  4908.5 2402.74  4918.5 2400.67  4928.6 2399.29  4938.6 2398.65
  4968.7 2398.17  4987.2 2399.47  4998.8 2399.66  5008.8 2399.30  5016.7 2397.41
  5017.0 2396.91  5020.6 2396.91  5020.9 2397.41  5028.8 2397.60  5048.8 2400.20
  5068.8 2400.38  5118.9 2402.80  5179.0 2404.73  5249.1 2409.21  5269.1 2410.91
  5309.1 2413.19  5349.2 2415.32  5372.0 2415.66  5379.2 2416.36  5404.8 2417.30
#Mann=3,-1,0
  4672.2    0.07       0  5016.7    0.07       0  5020.9    0.07       0
Bank Sta=5016.7,5020.9
Exp/Cntr=0.3,0.1

Type RM Length L Ch R = 1,33829,186,186,186
BEGIN DESCRIPTION:
Little Elm Creek 2 33828.77
END DESCRIPTION:
XS GIS Cut Line= 3
      1492605.00      6763588.00      1492684.83      6763287.73
      1492579.48      6762959.63
#Sta/Elev= 30
  4689.3 2413.08  4712.0 2411.06  4781.9 2407.04  4792.8 2405.51  4862.2 2399.56
  4937.4 2397.67  4942.6 2396.92  4948.0 2395.23  4958.3 2394.15  4977.5 2393.63
  4980.6 2392.92  4980.9 2392.42  4984.6 2392.42  4984.9 2392.92  4997.3 2394.77
  5031.2 2395.65  5047.7 2400.39  5053.0 2400.90  5062.7 2403.61  5073.2 2405.27
  5079.8 2404.91  5085.1 2403.28  5112.0 2403.05  5136.3 2404.66  5149.3 2406.42
  5181.4 2407.86  5208.3 2410.17  5213.5 2410.01  5262.3 2413.43  5344.6 2416.48
#Mann=3,-1,0
  4689.3    0.07       0  4980.6    0.07       0  4984.9    0.07       0
Bank Sta=4980.6,4984.9
Exp/Cntr=0.3,0.1

Type RM Length L Ch R = 1,33643,162,162,162
BEGIN DESCRIPTION:
Little Elm Creek 2 33642.93
END DESCRIPTION:
XS GIS Cut Line= 3
      1493076.33      6763512.63      1492841.96      6763301.70
      1492606.05      6762941.36
#Sta/Elev= 30
  4683.5 2418.25  4766.0 2416.48  4793.6 2415.31  4836.2 2411.64  4900.5 2407.58
  4907.2 2406.44  4935.6 2404.39  4956.6 2401.90  4964.0 2401.47  4970.8 2398.91
  4978.2 2397.49  4985.0 2394.29  4992.4 2392.85  4995.6 2391.10  4995.9 2390.60
  4999.7 2390.60  5000.0 2391.10  5036.0 2391.37  5051.0 2392.07  5063.1 2394.45
  5108.4 2395.27  5114.4 2396.05  5129.5 2396.84  5135.4 2399.27  5158.6 2400.74
  5186.7 2403.36  5216.9 2404.93  5280.2 2410.32  5325.5 2412.93  5429.5 2416.98
#Mann=3,-1,0
  4683.5    0.07       0  4995.6    0.07       0  5000.0    0.07       0
Bank Sta=4995.6,5000
Exp/Cntr=0.3,0.1

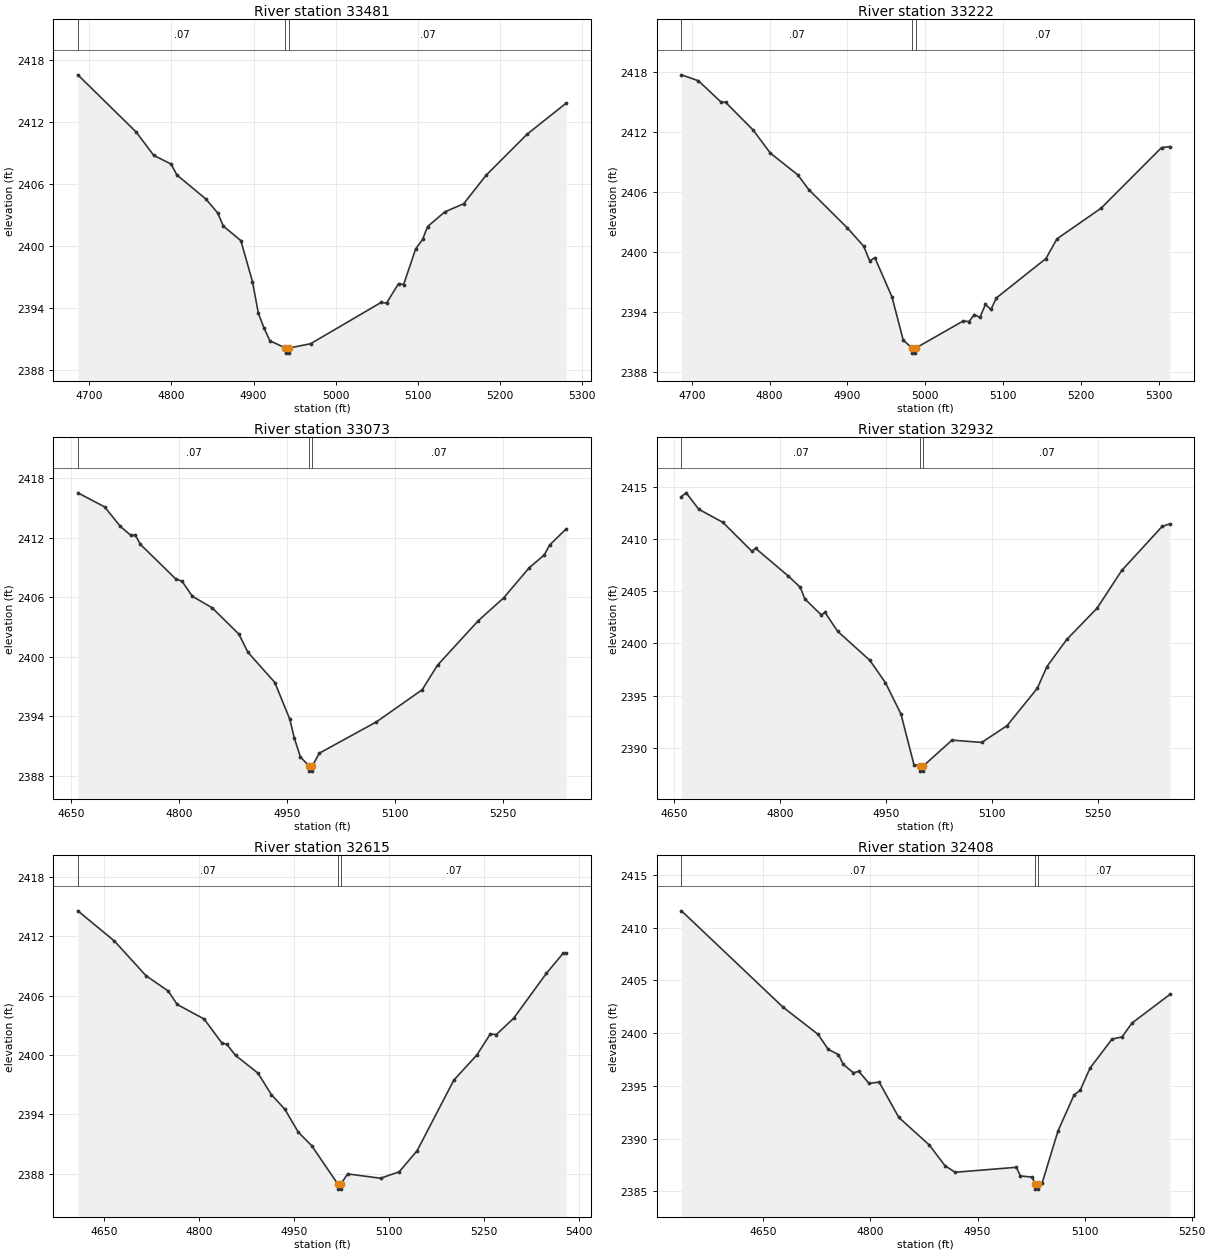
Type RM Length L Ch R = 1,33481,259,259,259
BEGIN DESCRIPTION:
Little Elm Creek 2 33481.23
END DESCRIPTION:
XS GIS Cut Line= 3
      1493125.80      6763387.62      1492901.86      6763158.48
      1492738.88      6762938.59
#Sta/Elev= 30
  4686.3 2416.60  4757.3 2411.05  4778.6 2408.79  4799.7 2407.95  4806.8 2406.89
  4842.1 2404.55  4856.3 2403.22  4863.4 2401.92  4884.6 2400.52  4898.7 2396.55
  4905.9 2393.48  4912.8 2392.04  4920.0 2390.80  4938.9 2390.11  4939.2 2389.61
  4943.0 2389.61  4943.3 2390.11  4969.4 2390.52  5055.5 2394.54  5061.8 2394.46
  5076.4 2396.35  5082.6 2396.26  5097.2 2399.71  5105.6 2400.63  5111.8 2401.89
  5132.7 2403.31  5155.7 2404.10  5182.8 2406.85  5232.9 2410.85  5280.4 2413.86
#Mann=3,-1,0
  4686.3    0.07       0  4938.9    0.07       0  4943.3    0.07       0
Bank Sta=4938.9,4943.3
Exp/Cntr=0.3,0.1

Type RM Length L Ch R = 1,33222,149,149,149
BEGIN DESCRIPTION:
Little Elm Creek 2 33222.26
END DESCRIPTION:
XS GIS Cut Line= 3
      1493295.11      6763338.19      1493097.17      6763098.58
      1492873.22      6762874.63
#Sta/Elev= 30
  4686.7 2417.68  4708.4 2417.09  4737.1 2414.99  4743.6 2414.92  4778.7 2412.17
  4800.9 2409.86  4836.1 2407.69  4850.4 2406.20  4899.9 2402.38  4920.7 2400.57
  4928.6 2399.09  4935.1 2399.42  4957.2 2395.49  4971.6 2391.18  4983.1 2390.38
  4983.4 2389.88  4987.2 2389.88  4987.5 2390.38  5048.9 2393.10  5056.0 2393.03
  5063.1 2393.73  5070.1 2393.44  5077.2 2394.74  5084.3 2394.24  5091.4 2395.40
  5155.0 2399.33  5169.1 2401.29  5225.7 2404.35  5303.5 2410.41  5314.2 2410.51
#Mann=3,-1,0
  4686.7    0.07       0  4983.1    0.07       0  4987.5    0.07       0
Bank Sta=4983.1,4987.5
Exp/Cntr=0.3,0.1

Type RM Length L Ch R = 1,33073,141,141,141
BEGIN DESCRIPTION:
Little Elm Creek 2 33072.66
END DESCRIPTION:
XS GIS Cut Line= 3
      1493407.09      6763267.87      1493203.94      6762994.41
      1492959.56      6762760.43
#Sta/Elev= 30
  4659.2 2416.51  4696.4 2415.10  4718.2 2413.14  4732.9 2412.23  4739.1 2412.25
  4746.2 2411.32  4796.1 2407.79  4803.8 2407.64  4818.4 2406.10  4845.9 2404.94
  4883.1 2402.29  4895.7 2400.46  4933.1 2397.42  4954.0 2393.70  4960.2 2391.81
  4968.6 2389.94  4980.7 2389.00  4981.0 2388.50  4984.8 2388.50  4985.2 2389.00
  4994.8 2390.30  5074.4 2393.46  5137.9 2396.69  5159.3 2399.17  5215.9 2403.64
  5251.1 2405.93  5286.7 2408.97  5307.7 2410.26  5315.0 2411.25  5338.2 2412.89
#Mann=3,-1,0
  4659.2    0.07       0  4980.7    0.07       0  4985.2    0.07       0
Bank Sta=4980.7,4985.2
Exp/Cntr=0.3,0.1

Type RM Length L Ch R = 1,32932,317,317,317
BEGIN DESCRIPTION:
Little Elm Creek 2 32931.81
END DESCRIPTION:
XS GIS Cut Line= 3
      1493461.75      6763231.38      1493326.34      6762929.31
      1493052.88      6762694.92
#Sta/Elev= 30
  4660.1 2414.07  4666.8 2414.43  4684.5 2412.86  4718.7 2411.60  4759.6 2408.84
  4765.0 2409.11  4811.4 2406.45  4828.2 2405.38  4834.6 2404.27  4857.8 2402.74
  4863.2 2402.97  4881.0 2401.17  4926.8 2398.37  4948.7 2396.24  4970.7 2393.24
  4989.1 2388.38  4997.9 2388.26  4998.3 2387.76  5002.1 2387.76  5002.4 2388.26
  5043.0 2390.73  5085.1 2390.51  5120.9 2392.12  5163.7 2395.70  5177.3 2397.78
  5205.4 2400.38  5248.2 2403.37  5283.3 2407.00  5340.4 2411.21  5351.3 2411.46
#Mann=3,-1,0
  4660.1    0.07       0  4997.9    0.07       0  5002.4    0.07       0
Bank Sta=4997.9,5002.4
Exp/Cntr=0.3,0.1

Type RM Length L Ch R = 1,32615,207,207,207
BEGIN DESCRIPTION:
Little Elm Creek 2 32614.79
END DESCRIPTION:
XS GIS Cut Line= 3
      1493808.11      6762986.60      1493539.88      6762713.16
      1493211.77      6762507.45
#Sta/Elev= 30
  4609.2 2414.57  4667.0 2411.51  4716.5 2408.02  4751.8 2406.46  4766.0 2405.10
  4808.4 2403.63  4836.7 2401.18  4843.8 2401.10  4858.0 2399.95  4893.3 2398.16
  4914.5 2395.98  4935.7 2394.51  4957.0 2392.18  4978.1 2390.82  5019.4 2386.93
  5019.7 2386.43  5023.6 2386.43  5023.9 2386.93  5034.7 2387.97  5086.6 2387.53
  5116.0 2388.18  5144.3 2390.31  5202.1 2397.44  5238.6 2400.00  5259.8 2402.12
  5269.2 2402.06  5296.4 2403.69  5348.2 2408.25  5374.7 2410.28  5379.5 2410.28
#Mann=3,-1,0
  4609.2    0.07       0  5019.4    0.07       0  5023.9    0.07       0
Bank Sta=5019.4,5023.9
Exp/Cntr=0.3,0.1

Type RM Length L Ch R = 1,32408,115,115,115
BEGIN DESCRIPTION:
Little Elm Creek 2 32407.751
END DESCRIPTION:
XS GIS Cut Line= 3
      1493854.99      6762887.99      1493551.11      6762536.42
      1493355.02      6762438.01
#Sta/Elev= 30
  4535.3 2411.59  4677.3 2402.47  4726.7 2399.87  4740.9 2398.45  4755.2 2397.96
  4761.8 2397.04  4776.1 2396.23  4783.7 2396.37  4798.0 2395.23  4812.2 2395.35
  4839.7 2392.00  4882.5 2389.38  4904.4 2387.42  4918.6 2386.80  5004.4 2387.27
  5010.0 2386.45  5026.8 2386.34  5030.1 2385.70  5030.4 2385.20  5034.3 2385.20
  5034.7 2385.70  5040.4 2385.76  5062.8 2390.74  5085.2 2394.13  5093.8 2394.58
  5107.5 2396.67  5138.4 2399.43  5152.3 2399.63  5166.4 2400.95  5219.4 2403.66
#Mann=3,-1,0
  4535.3    0.07       0  5030.1    0.07       0  5034.7    0.07       0
Bank Sta=5030.1,5034.7
Exp/Cntr=0.3,0.1

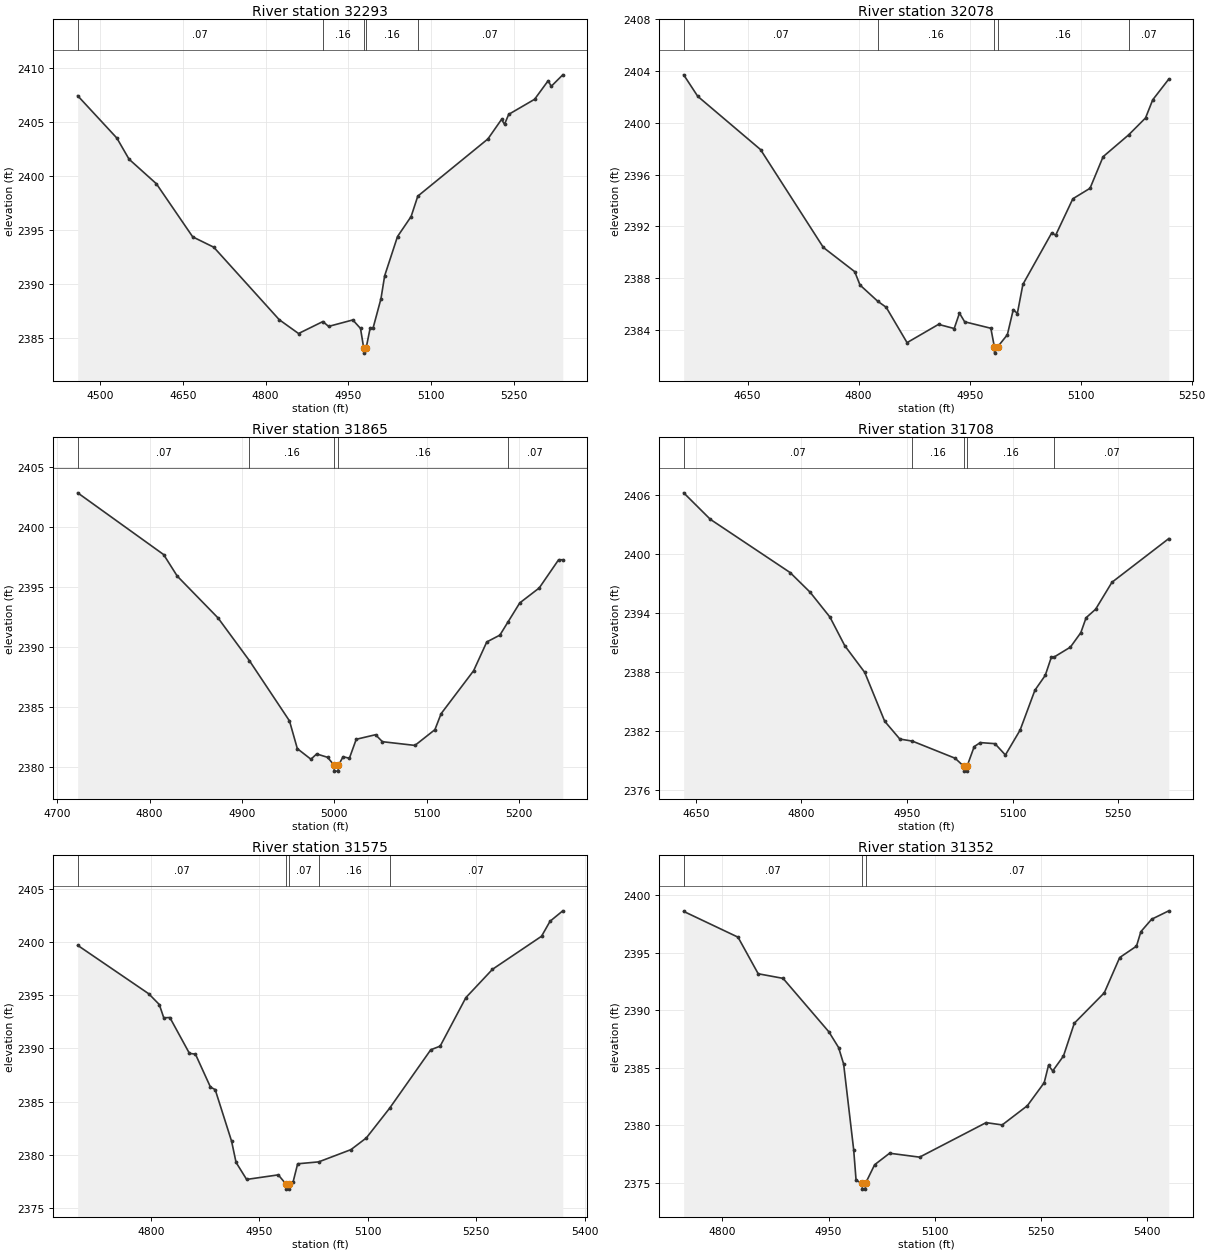
Type RM Length L Ch R = 1,32293,215,215,215
BEGIN DESCRIPTION:
Little Elm Creek 2 32292.55
END DESCRIPTION:
XS GIS Cut Line= 3
      1494047.70      6762679.31      1493578.94      6762429.31
      1493253.38      6762304.29
#Sta/Elev= 30
  4459.1 2407.46  4530.2 2403.53  4552.3 2401.57  4601.9 2399.29  4667.8 2394.36
  4706.0 2393.40  4824.8 2386.67  4859.8 2385.39  4903.9 2386.50  4914.3 2386.05
  4958.2 2386.65  4972.2 2385.86  4977.9 2384.07  4978.2 2383.57  4982.5 2384.07
  4989.8 2385.92  4995.1 2385.92  5009.3 2388.62  5016.0 2390.75  5039.3 2394.39
  5064.0 2396.25  5076.1 2398.14  5203.3 2403.45  5228.0 2405.26  5233.4 2404.81
  5241.0 2405.73  5288.0 2407.13  5312.7 2408.86  5318.1 2408.33  5339.1 2409.40
#Mann=5,-1,0
  4459.1    0.07       0  4903.9    0.16       0  4977.9    0.07       0
  4982.5    0.16       0  5076.1    0.07       0
Bank Sta=4977.9,4982.5
Exp/Cntr=0.3,0.1

Type RM Length L Ch R = 1,32078,213,213,213
BEGIN DESCRIPTION:
Little Elm Creek 2 32077.75
END DESCRIPTION:
XS GIS Cut Line= 3
      1494013.86      6762596.00      1493706.55      6762291.29
      1493615.41      6762088.17
#Sta/Elev= 30
  4563.6 2403.71  4582.6 2402.05  4667.4 2397.94  4752.3 2390.38  4794.7 2388.51
  4801.8 2387.48  4825.7 2386.23  4837.2 2385.76  4865.4 2383.03  4907.9 2384.44
  4929.1 2384.12  4936.2 2385.31  4943.2 2384.64  4978.6 2384.14  4983.3 2382.72
  4983.6 2382.22  4988.0 2382.72  5000.9 2383.64  5008.9 2385.58  5014.4 2385.28
  5021.9 2387.53  5060.7 2391.49  5066.2 2391.33  5089.4 2394.14  5112.6 2394.95
  5130.3 2397.39  5164.9 2399.08  5187.6 2400.38  5197.3 2401.78  5219.0 2403.38
#Mann=5,-1,0
  4563.6    0.07       0  4825.7    0.16       0  4983.3    0.07       0
  4988.0    0.16       0  5164.9    0.07       0
Bank Sta=4983.3,4988
Exp/Cntr=0.3,0.1

Type RM Length L Ch R = 1,31865,157,157,157
BEGIN DESCRIPTION:
Little Elm Creek 2 31865.11
END DESCRIPTION:
XS GIS Cut Line= 3
      1494081.53      6762512.61      1493922.69      6762293.89
      1493750.79      6762106.37
#Sta/Elev= 30
  4722.3 2402.83  4815.3 2397.69  4830.0 2395.90  4874.1 2392.42  4908.0 2388.87
  4951.4 2383.85  4959.9 2381.54  4974.6 2380.66  4980.8 2381.10  4992.6 2380.82
  4999.6 2380.17  4999.9 2379.67  5004.0 2379.67  5004.4 2380.17  5009.4 2380.87
  5016.2 2380.74  5023.6 2382.32  5044.5 2382.70  5051.9 2382.12  5087.1 2381.81
  5108.7 2383.12  5115.4 2384.45  5150.6 2388.03  5164.8 2390.42  5179.0 2390.99
  5187.4 2392.04  5200.5 2393.67  5221.5 2394.91  5242.5 2397.26  5247.0 2397.26
#Mann=5,-1,0
  4722.3    0.07       0  4908.0    0.16       0  4999.6    0.07       0
  5004.4    0.16       0  5187.4    0.07       0
Bank Sta=4999.6,5004.4
Exp/Cntr=0.3,0.1

Type RM Length L Ch R = 1,31708,133,133,133
BEGIN DESCRIPTION:
Little Elm Creek 2 31708.46
END DESCRIPTION:
XS GIS Cut Line= 3
      1494279.43      6762437.09      1494013.84      6762187.12
      1493749.08      6762000.23
#Sta/Elev= 30
  4632.9 2406.20  4670.7 2403.51  4784.0 2398.10  4812.3 2396.11  4840.6 2393.57
  4861.6 2390.67  4890.0 2387.95  4918.3 2382.99  4939.8 2381.18  4957.6 2380.97
  5018.3 2379.23  5030.5 2378.42  5030.9 2377.92  5035.0 2377.92  5035.3 2378.42
  5045.4 2380.41  5054.0 2380.82  5074.9 2380.71  5089.7 2379.56  5110.6 2382.09
  5131.6 2386.14  5146.3 2387.65  5155.0 2389.51  5158.8 2389.51  5182.0 2390.52
  5196.8 2391.99  5204.3 2393.51  5217.8 2394.37  5241.0 2397.11  5321.7 2401.55
#Mann=5,-1,0
  4632.9    0.07       0  4957.6    0.16       0  5030.5    0.07       0
  5035.3    0.16       0  5158.8    0.07       0
Bank Sta=5030.5,5035.3
Exp/Cntr=0.3,0.1

Type RM Length L Ch R = 1,31575,223,223,223
BEGIN DESCRIPTION:
Little Elm Creek 2 31575.07
END DESCRIPTION:
XS GIS Cut Line= 3
      1494347.20      6762273.08      1494107.59      6762093.37
      1493789.96      6761900.71
#Sta/Elev= 30
  4698.6 2399.67  4796.9 2395.12  4811.5 2394.11  4817.7 2392.86  4826.1 2392.89
  4853.2 2389.52  4861.5 2389.45  4882.3 2386.35  4888.8 2386.12  4911.5 2381.27
  4917.7 2379.28  4932.3 2377.68  4976.1 2378.11  4986.4 2377.27  4986.8 2376.77
  4990.9 2376.77  4991.2 2377.27  4996.6 2377.45  5002.9 2379.15  5032.0 2379.33
  5076.6 2380.48  5097.9 2381.58  5130.1 2384.37  5187.0 2389.86  5200.0 2390.20
  5235.6 2394.76  5272.4 2397.42  5340.2 2400.52  5352.0 2401.93  5369.6 2402.91
#Mann=5,-1,0
  4698.6    0.07       0  4986.4    0.07       0  4991.2    0.07       0
  5032.0    0.16       0  5130.1    0.07       0
Bank Sta=4986.4,4991.2
Exp/Cntr=0.3,0.1

Type RM Length L Ch R = 1,31352,207,207,207
BEGIN DESCRIPTION:
Little Elm Creek 2 31352.11
END DESCRIPTION:
XS GIS Cut Line= 3
      1494448.75      6762202.76      1494287.28      6762017.85
      1493916.56      6761781.94
#Sta/Elev= 30
  4745.5 2398.59  4822.2 2396.35  4850.7 2393.17  4885.8 2392.77  4950.4 2388.13
  4964.2 2386.76  4971.3 2385.33  4985.5 2377.88  4988.9 2375.22  4997.4 2374.95
  4997.8 2374.45  5001.9 2374.45  5002.2 2374.95  5015.1 2376.57  5036.2 2377.57
  5078.6 2377.23  5172.5 2380.23  5195.2 2380.03  5230.7 2381.70  5254.5 2383.70
  5260.6 2385.21  5266.5 2384.72  5281.7 2386.02  5297.0 2388.87  5339.3 2391.51
  5361.1 2394.58  5384.8 2395.57  5391.0 2396.83  5406.2 2397.91  5430.4 2398.64
#Mann=3,-1,0
  4745.5    0.07       0  4997.4    0.07       0  5002.2    0.07       0
Bank Sta=4997.4,5002.2
Exp/Cntr=0.3,0.1

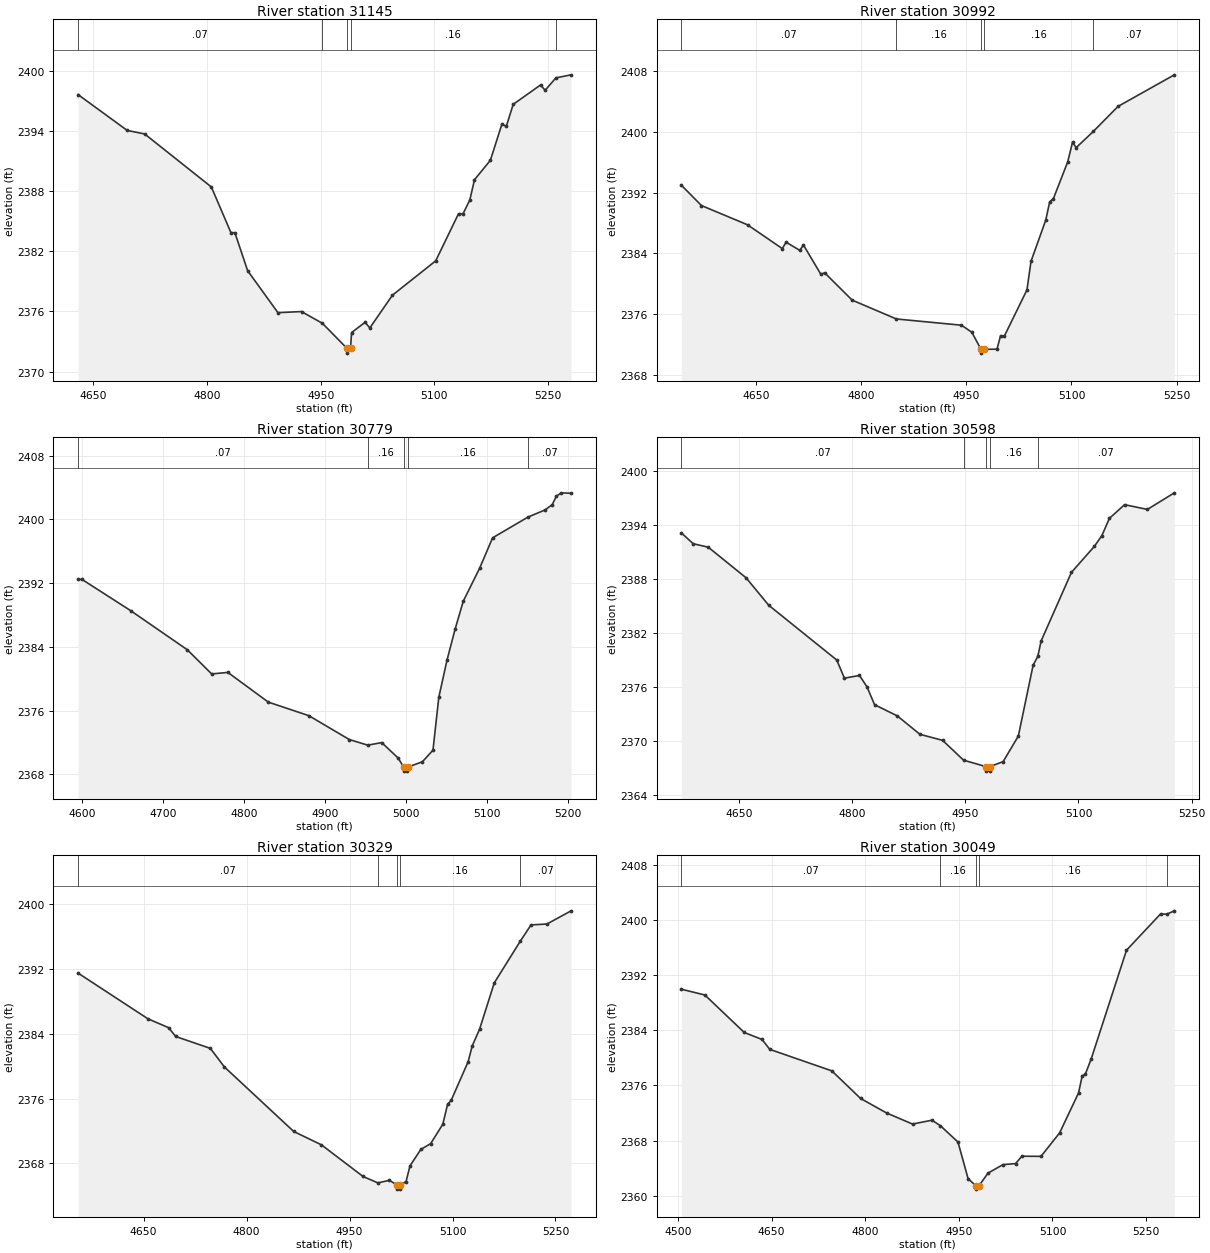
Type RM Length L Ch R = 1,31145,153,153,153
BEGIN DESCRIPTION:
Little Elm Creek 2 31144.77
END DESCRIPTION:
XS GIS Cut Line= 3
      1494487.80      6762179.31      1494368.01      6761835.56
      1494209.59      6761596.63
#Sta/Elev= 30
  4629.8 2397.60  4694.7 2394.03  4717.7 2393.68  4805.7 2388.40  4831.5 2383.86
  4836.8 2383.84  4853.6 2380.06  4893.6 2375.88  4924.7 2375.99  4952.3 2374.82
  4984.4 2372.35  4984.8 2371.85  4989.4 2372.35  4990.8 2373.90  5008.6 2374.92
  5014.9 2374.36  5044.7 2377.62  5101.8 2381.04  5131.9 2385.73  5137.9 2385.73
  5146.9 2387.12  5153.0 2389.12  5174.0 2391.06  5189.1 2394.64  5195.1 2394.46
  5204.1 2396.63  5240.2 2398.56  5246.2 2398.03  5260.5 2399.27  5280.5 2399.57
#Mann=5,-1,0
  4629.8    0.07       0  4952.3    0.16       0  4984.4    0.07       0
  4989.4    0.16       0  5260.5    0.07       0
Bank Sta=4984.4,4989.4
Exp/Cntr=0.3,0.1

Type RM Length L Ch R = 1,30992,213,213,213
BEGIN DESCRIPTION:
Little Elm Creek 2 30992.3
END DESCRIPTION:
XS GIS Cut Line= 3
      1494641.45      6762166.30      1494482.59      6761744.41
      1494407.19      6761502.60
#Sta/Elev= 30
  4542.8 2392.98  4571.5 2390.30  4637.3 2387.77  4687.0 2384.64  4692.4 2385.48
  4711.9 2384.41  4717.2 2385.11  4742.1 2381.26  4747.5 2381.46  4786.7 2377.87
  4849.9 2375.39  4942.9 2374.57  4957.7 2373.64  4970.7 2371.40  4971.1 2370.90
  4975.7 2371.40  4993.6 2371.42  4998.7 2373.19  5003.9 2373.10  5036.4 2379.21
  5042.2 2382.97  5063.2 2388.37  5068.9 2390.79  5074.2 2391.22  5094.6 2396.04
  5101.5 2398.62  5106.7 2397.91  5131.2 2400.04  5166.5 2403.33  5246.9 2407.48
#Mann=5,-1,0
  4542.8    0.07       0  4849.9    0.16       0  4970.7    0.07       0
  4975.7    0.16       0  5131.2    0.07       0
Bank Sta=4970.7,4975.7
Exp/Cntr=0.3,0.1

Type RM Length L Ch R = 1,30779,181,181,181
BEGIN DESCRIPTION:
Little Elm Creek 2 30779.33
END DESCRIPTION:
XS GIS Cut Line= 3
      1494703.94      6762142.82      1494693.53      6761734.00
      1494667.48      6761536.06
#Sta/Elev= 30
  4594.9 2392.47  4599.8 2392.47  4659.7 2388.56  4729.8 2383.64  4759.8 2380.61
  4779.8 2380.80  4829.8 2377.07  4879.8 2375.37  4929.8 2372.37  4952.5 2371.67
  4969.8 2371.99  4989.9 2370.06  4996.9 2368.91  4997.2 2368.41  5001.5 2368.41
  5001.9 2368.91  5020.0 2369.59  5033.0 2371.04  5040.2 2377.67  5050.3 2382.33
  5060.3 2386.22  5070.4 2389.74  5090.6 2393.88  5106.6 2397.69  5150.2 2400.29
  5171.3 2401.19  5180.3 2401.87  5185.3 2402.91  5191.5 2403.34  5203.5 2403.28
#Mann=5,-1,0
  4594.9    0.07       0  4952.5    0.16       0  4996.9    0.07       0
  5001.9    0.16       0  5150.2    0.07       0
Bank Sta=4996.9,5001.9
Exp/Cntr=0.3,0.1

Type RM Length L Ch R = 1,30598,269,269,269
BEGIN DESCRIPTION:
Little Elm Creek 2 30598.11
END DESCRIPTION:
XS GIS Cut Line= 3
      1494854.98      6762163.69      1494875.82      6761747.02
      1494850.05      6761512.52
#Sta/Elev= 30
  4573.9 2393.16  4589.6 2391.95  4609.6 2391.56  4659.7 2388.15  4689.7 2385.09
  4779.8 2378.99  4789.9 2376.97  4809.9 2377.27  4819.9 2375.99  4829.9 2374.01
  4859.9 2372.77  4890.0 2370.71  4920.0 2370.04  4947.8 2367.83  4977.6 2367.11
  4977.9 2366.61  4982.2 2366.61  4982.6 2367.11  5000.2 2367.67  5020.3 2370.51
  5039.9 2378.41  5046.2 2379.41  5050.5 2381.11  5090.7 2388.76  5120.9 2391.64
  5130.9 2392.84  5141.0 2394.78  5161.1 2396.30  5191.3 2395.77  5227.0 2397.62
#Mann=5,-1,0
  4573.9    0.07       0  4947.8    0.16       0  4977.6    0.07       0
  4982.6    0.16       0  5046.2    0.07       0
Bank Sta=4977.6,4982.6
Exp/Cntr=0.3,0.1

Type RM Length L Ch R = 1,30329,280,280,280
BEGIN DESCRIPTION:
Little Elm Creek 2 30328.86
END DESCRIPTION:
XS GIS Cut Line= 3
      1495039.89      6762228.75      1495104.98      6761791.29
      1495203.93      6761533.50
#Sta/Elev= 30
  4554.4 2391.50  4656.3 2385.85  4686.3 2384.76  4696.7 2383.67  4747.2 2382.20
  4767.5 2379.92  4868.6 2371.94  4909.0 2370.29  4969.7 2366.38  4991.3 2365.59
  5008.1 2365.91  5019.1 2365.32  5019.4 2364.82  5023.8 2364.82  5024.2 2365.32
  5032.3 2365.76  5038.1 2367.70  5053.8 2369.72  5068.2 2370.44  5085.9 2372.84
  5092.8 2375.28  5098.2 2375.81  5122.8 2380.56  5128.7 2382.50  5139.4 2384.56
  5160.9 2390.30  5198.7 2395.43  5214.4 2397.45  5237.6 2397.56  5272.8 2399.19
#Mann=5,-1,0
  4554.4    0.07       0  4991.3    0.16       0  5019.1    0.07       0
  5024.2    0.16       0  5198.7    0.07       0
Bank Sta=5019.1,5024.2
Exp/Cntr=0.3,0.1

Type RM Length L Ch R = 1,30049,176,176,176
BEGIN DESCRIPTION:
Little Elm Creek 2 30048.55
END DESCRIPTION:
XS GIS Cut Line= 3
      1495193.52      6762364.22      1495328.94      6761890.25
      1495370.60      6761596.02
#Sta/Elev= 30
  4505.2 2389.95  4542.9 2389.11  4606.0 2383.68  4634.6 2382.66  4646.9 2381.23
  4746.4 2378.11  4792.5 2374.11  4834.1 2372.01  4875.7 2370.40  4906.9 2370.96
  4920.5 2370.15  4948.5 2367.80  4964.8 2362.48  4977.1 2361.47  4977.5 2360.97
  4982.3 2361.47  4996.7 2363.29  5020.6 2364.52  5040.8 2364.67  5050.9 2365.74
  5081.6 2365.72  5111.5 2369.13  5141.8 2374.92  5147.6 2377.39  5152.6 2377.63
  5162.0 2379.83  5218.6 2395.60  5273.1 2400.85  5283.3 2400.83  5295.3 2401.31
#Mann=5,-1,0
  4505.2    0.07       0  4920.5    0.16       0  4977.1    0.07       0
  4982.3    0.16       0  5283.3    0.07       0
Bank Sta=4977.1,4982.3
Exp/Cntr=0.3,0.1