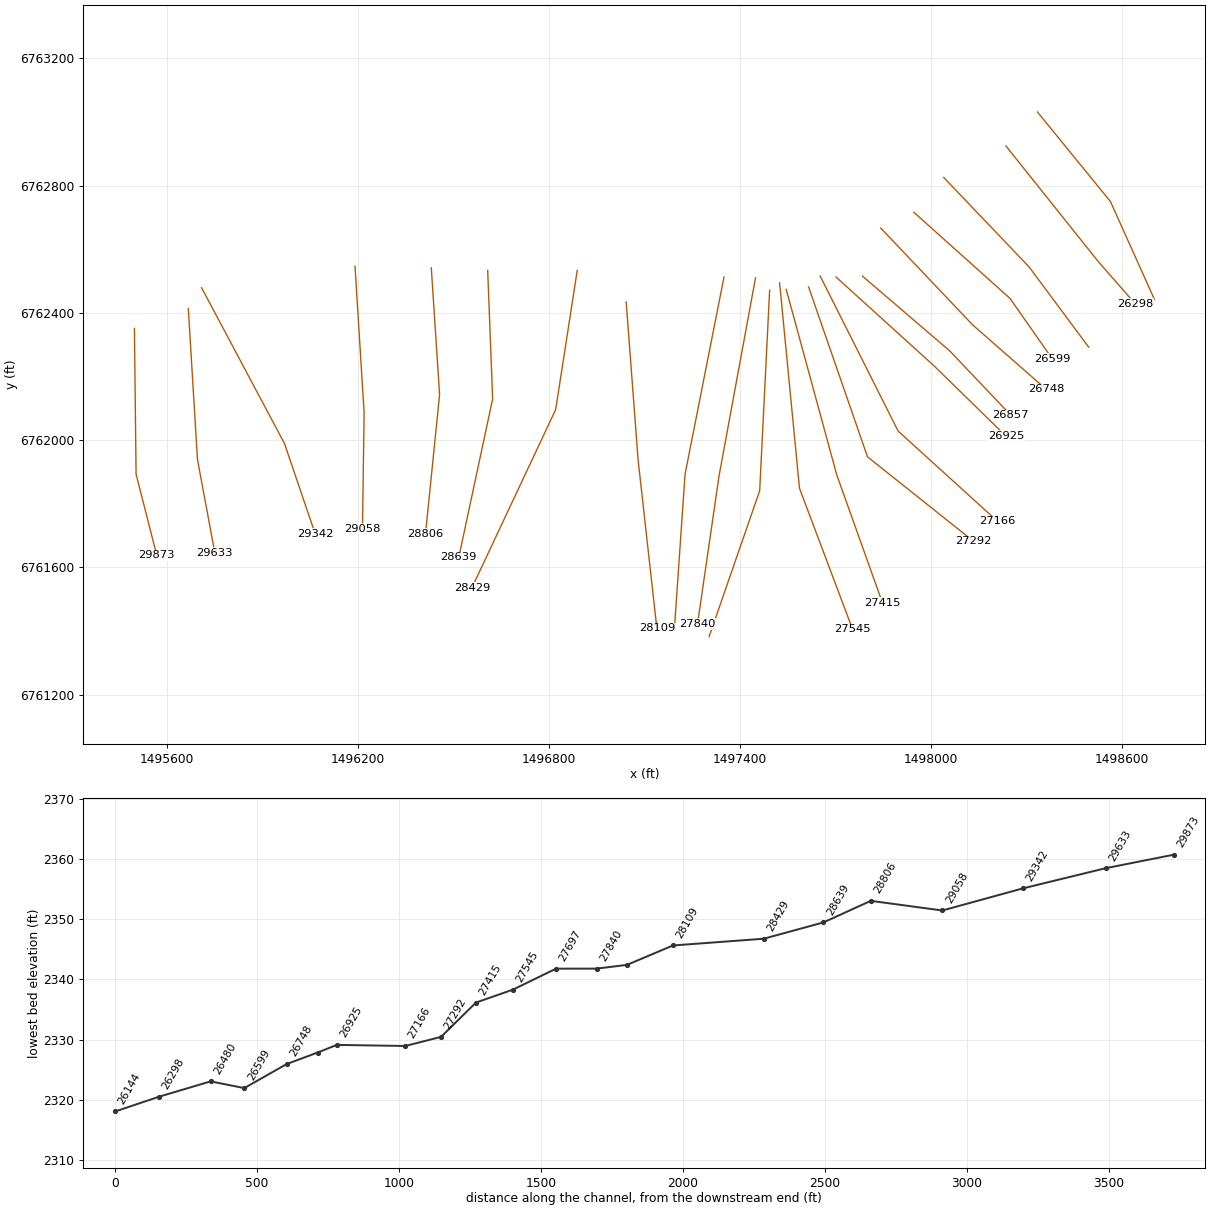
HEC-RAS study Little Elm Creek 2.prj: Little Elm Creek 2 Base Level Engineering

--- Little Elm Creek 2.g01 (geometry) --- (continued)

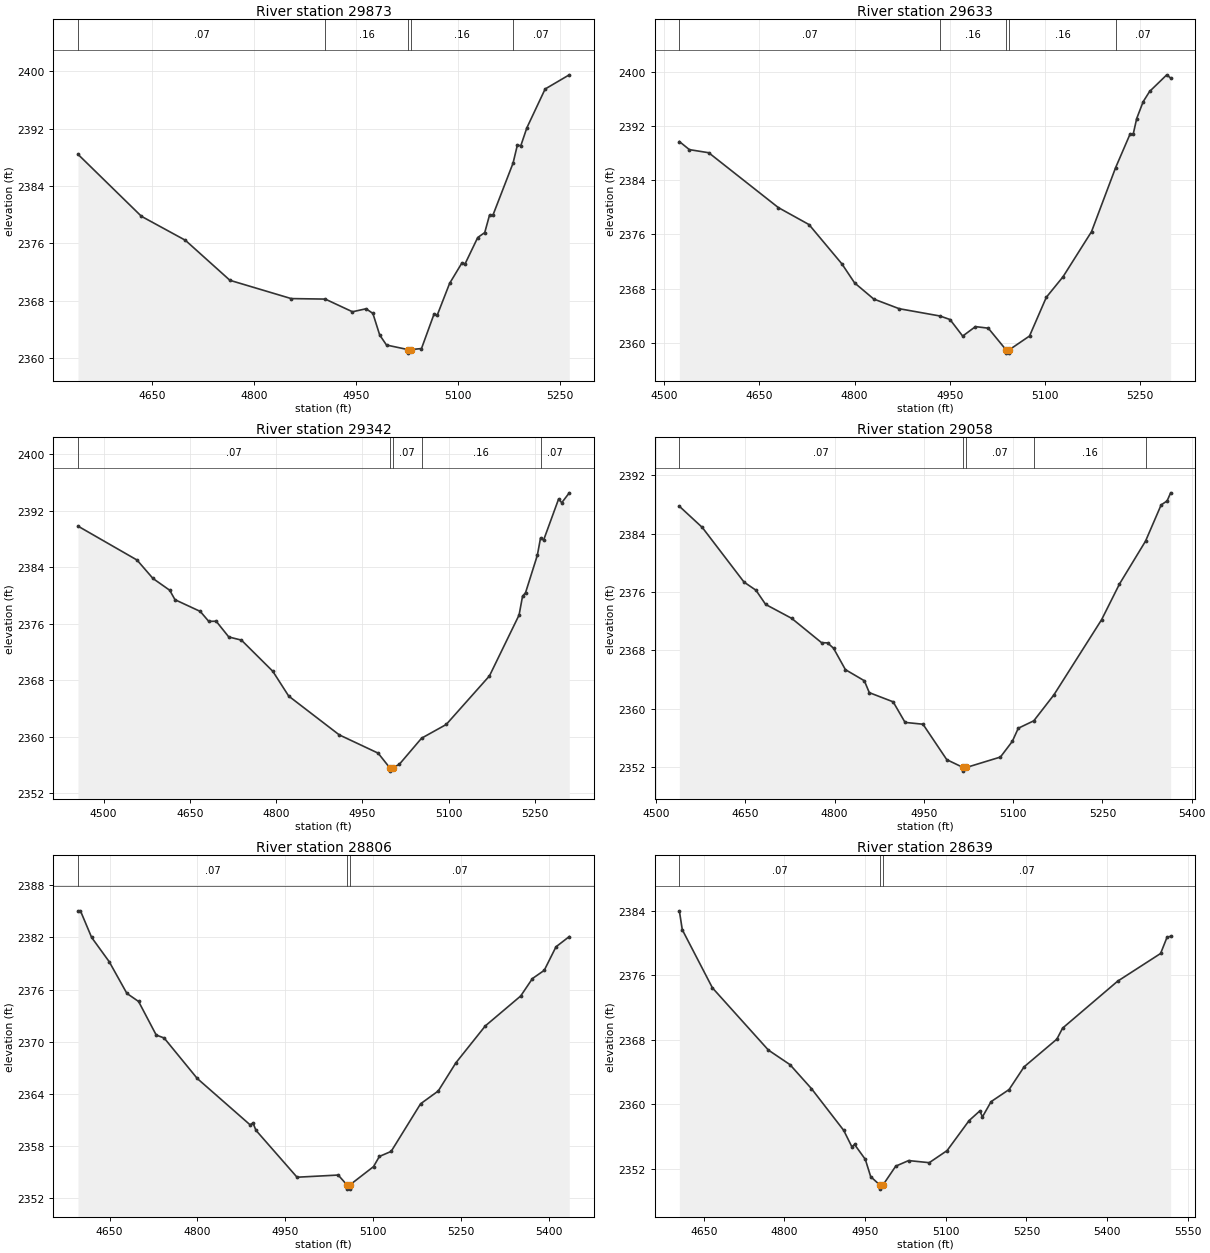
Type RM Length L Ch R = 1,29873,240,240,240
BEGIN DESCRIPTION:
Little Elm Creek 2 29873.39
END DESCRIPTION:
XS GIS Cut Line= 3
      1495498.21      6762351.18      1495503.42      6761892.85
      1495568.52      6761637.68
#Sta/Elev= 30
  4541.6 2388.43  4634.8 2379.78  4699.3 2376.44  4764.8 2370.85  4854.8 2368.30
  4904.8 2368.23  4944.8 2366.46  4964.8 2366.88  4974.8 2366.23  4984.8 2363.22
  4994.8 2361.82  5026.0 2361.19  5026.5 2360.69  5031.3 2361.19  5046.2 2361.33
  5064.4 2366.08  5069.5 2366.03  5087.5 2370.42  5105.2 2373.21  5110.4 2373.18
  5128.8 2376.82  5139.1 2377.51  5146.1 2379.93  5151.3 2379.98  5180.7 2387.20
  5187.0 2389.70  5192.1 2389.63  5201.0 2392.13  5227.8 2397.54  5263.3 2399.52
#Mann=5,-1,0
  4541.6    0.07       0  4904.8    0.16       0  5026.0    0.07       0
  5031.3    0.16       0  5180.7    0.07       0
Bank Sta=5026,5031.3
Exp/Cntr=0.3,0.1

Type RM Length L Ch R = 1,29633,291,291,291
BEGIN DESCRIPTION:
Little Elm Creek 2 29633.12
END DESCRIPTION:
XS GIS Cut Line= 3
      1495667.48      6762413.73      1495696.13      6761939.73
      1495750.82      6761645.43
#Sta/Elev= 30
  4523.9 2389.74  4539.7 2388.54  4570.2 2388.08  4679.9 2379.97  4728.2 2377.46
  4780.1 2371.64  4800.1 2368.83  4830.2 2366.45  4870.3 2365.02  4934.6 2363.94
  4950.4 2363.42  4970.4 2360.97  4990.5 2362.37  5010.7 2362.14  5038.6 2358.95
  5039.0 2358.45  5043.5 2358.45  5043.9 2358.95  5075.7 2360.98  5102.2 2366.71
  5128.5 2369.74  5173.4 2376.41  5211.3 2385.86  5234.1 2390.83  5239.2 2390.87
  5244.6 2393.14  5254.8 2395.63  5265.0 2397.15  5292.0 2399.60  5298.1 2399.12
#Mann=5,-1,0
  4523.9    0.07       0  4934.6    0.16       0  5038.6    0.07       0
  5043.9    0.16       0  5211.3    0.07       0
Bank Sta=5038.6,5043.9
Exp/Cntr=0.3,0.1

Type RM Length L Ch R = 1,29342,284,284,284
BEGIN DESCRIPTION:
Little Elm Creek 2 29342
END DESCRIPTION:
XS GIS Cut Line= 3
      1495709.14      6762478.81      1495969.57      6761989.20
      1496065.92      6761705.37
#Sta/Elev= 30
  4455.6 2389.84  4558.3 2385.03  4586.0 2382.42  4615.1 2380.75  4624.3 2379.41
  4668.2 2377.75  4683.0 2376.34  4695.9 2376.36  4717.8 2374.13  4739.8 2373.68
  4794.4 2369.26  4822.0 2365.75  4909.9 2360.25  4977.5 2357.66  4997.5 2355.61
  4997.9 2355.11  5002.8 2355.61  5014.1 2356.05  5053.1 2359.78  5095.9 2361.72
  5171.1 2368.61  5222.6 2377.24  5228.6 2379.89  5233.9 2380.42  5254.3 2385.69
  5259.9 2388.15  5265.3 2387.87  5291.4 2393.70  5296.7 2393.15  5309.9 2394.56
#Mann=5,-1,0
  4455.6    0.07       0  4997.5    0.07       0  5002.8    0.07       0
  5053.1    0.16       0  5259.9    0.07       0
Bank Sta=4997.5,5002.8
Exp/Cntr=0.3,0.1

Type RM Length L Ch R = 1,29058,252,252,252
BEGIN DESCRIPTION:
Little Elm Creek 2 29057.8
END DESCRIPTION:
XS GIS Cut Line= 3
      1496190.92      6762546.48      1496219.57      6762085.56
      1496214.37      6761722.00
#Sta/Elev= 30
  4539.3 2387.75  4577.9 2384.84  4648.0 2377.35  4668.0 2376.24  4684.3 2374.29
  4728.1 2372.38  4778.2 2369.05  4788.3 2369.02  4798.3 2368.29  4818.3 2365.35
  4850.1 2363.83  4858.4 2362.20  4898.5 2360.94  4918.5 2358.12  4948.6 2357.87
  4988.6 2353.01  5016.0 2351.94  5016.4 2351.44  5021.4 2351.94  5078.7 2353.37
  5098.7 2355.52  5108.7 2357.32  5134.8 2358.34  5168.7 2361.91  5248.7 2372.20
  5278.7 2377.09  5322.5 2382.97  5348.7 2387.93  5358.7 2388.48  5364.7 2389.59
#Mann=5,-1,0
  4539.3    0.07       0  5016.0    0.07       0  5021.4    0.07       0
  5134.8    0.16       0  5322.5    0.07       0
Bank Sta=5016,5021.4
Exp/Cntr=0.3,0.1

Type RM Length L Ch R = 1,28806,167,167,167
BEGIN DESCRIPTION:
Little Elm Creek 2 28805.68
END DESCRIPTION:
XS GIS Cut Line= 3
      1496430.50      6762541.29      1496456.55      6762142.85
      1496412.28      6761705.37
#Sta/Elev= 30
  4596.1 2385.06  4600.3 2385.06  4619.4 2382.00  4649.5 2379.20  4679.6 2375.56
  4699.6 2374.63  4729.7 2370.77  4743.2 2370.43  4799.8 2365.77  4890.0 2360.44
  4895.0 2360.65  4900.0 2359.81  4970.2 2354.41  5040.5 2354.66  5055.2 2353.54
  5055.7 2353.04  5060.3 2353.04  5060.7 2353.54  5100.8 2355.63  5110.8 2356.80
  5130.9 2357.38  5181.2 2362.86  5211.3 2364.33  5241.5 2367.58  5291.7 2371.82
  5352.1 2375.26  5372.2 2377.27  5392.3 2378.21  5412.4 2380.92  5435.1 2382.10
#Mann=3,-1,0
  4596.1    0.07       0  5055.2    0.07       0  5060.7    0.07       0
Bank Sta=5055.2,5060.7
Exp/Cntr=0.3,0.1

Type RM Length L Ch R = 1,28639,210,210,210
BEGIN DESCRIPTION:
Little Elm Creek 2 28638.88
END DESCRIPTION:
XS GIS Cut Line= 3
      1496607.59      6762533.50      1496623.21      6762129.83
      1496516.79      6761631.44
#Sta/Elev= 30
  4604.6 2383.97  4610.1 2381.62  4666.1 2374.42  4770.2 2366.70  4810.3 2364.90
  4850.3 2361.92  4910.3 2356.74  4925.4 2354.71  4930.4 2355.00  4950.4 2353.15
  4960.4 2351.01  4977.6 2349.96  4978.1 2349.46  4983.1 2349.96  5007.0 2352.31
  5030.9 2353.00  5069.3 2352.74  5102.5 2354.24  5143.4 2357.96  5163.2 2359.15
  5168.3 2358.43  5184.3 2360.31  5217.8 2361.81  5245.6 2364.62  5306.6 2368.06
  5317.2 2369.42  5419.5 2375.24  5499.5 2378.68  5511.5 2380.70  5518.2 2380.81
#Mann=3,-1,0
  4604.6    0.07       0  4977.6    0.07       0  4983.1    0.07       0
Bank Sta=4977.6,4983.1
Exp/Cntr=0.3,0.1

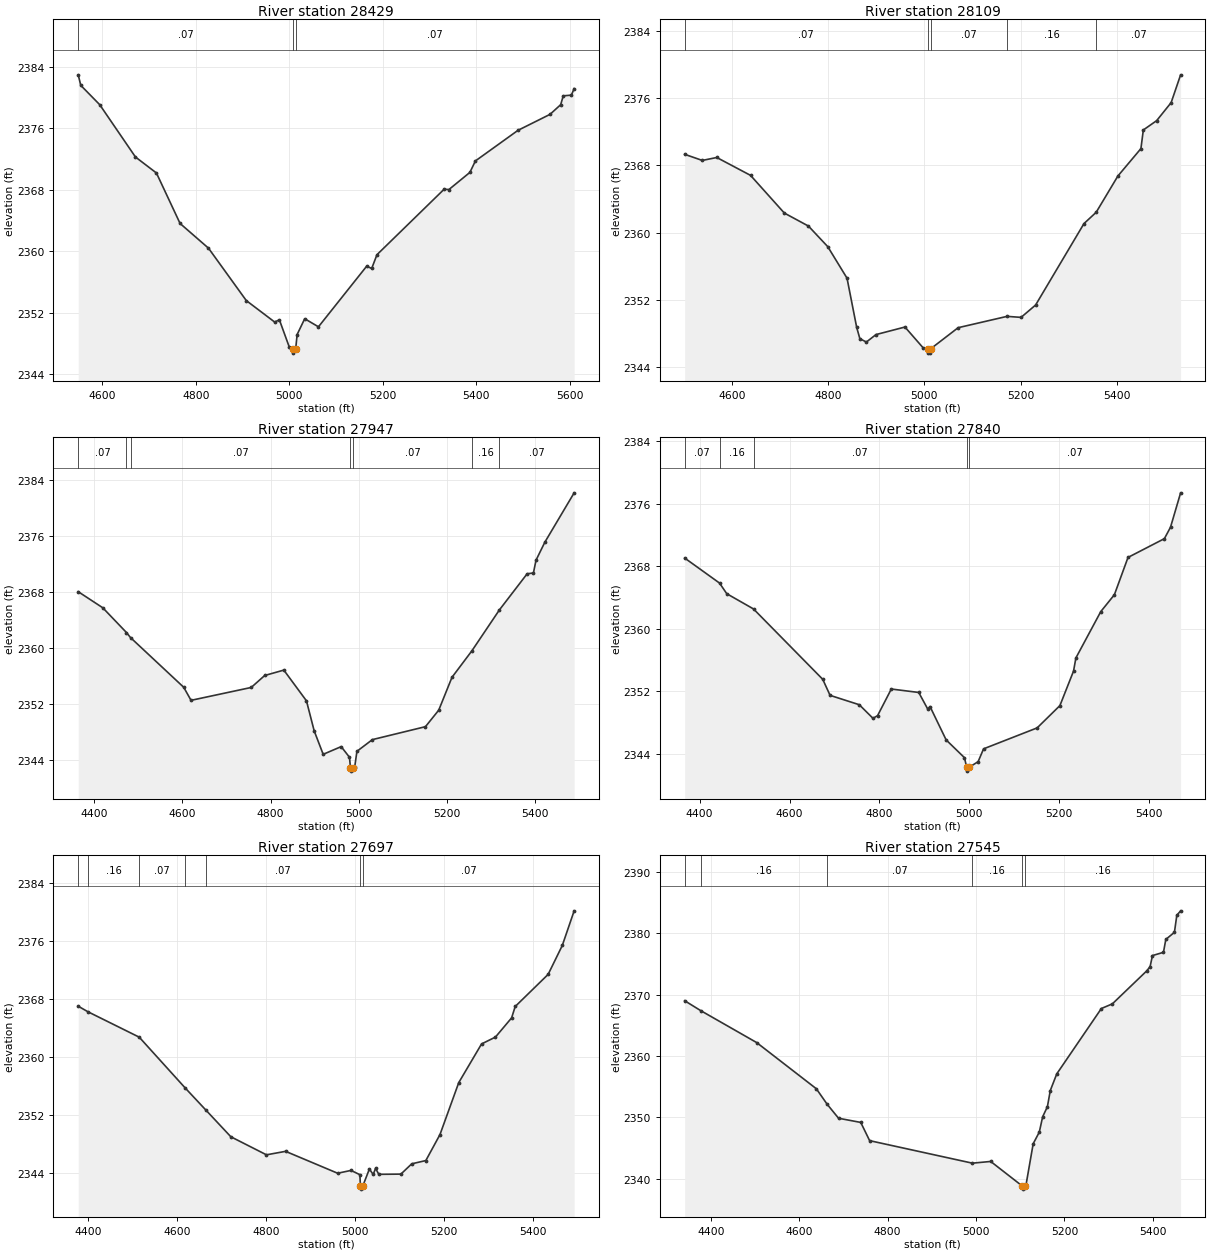
Type RM Length L Ch R = 1,28429,320,320,320
BEGIN DESCRIPTION:
Little Elm Creek 2 28428.94
END DESCRIPTION:
XS GIS Cut Line= 3
      1496888.84      6762533.48      1496821.13      6762095.98
      1496558.11      6761536.09
#Sta/Elev= 30
  4548.2 2382.93  4553.7 2381.56  4594.2 2379.05  4670.7 2372.25  4715.6 2370.17
  4766.2 2363.61  4827.0 2360.40  4907.9 2353.59  4968.6 2350.80  4978.7 2351.09
  4999.7 2347.58  5008.0 2347.26  5008.5 2346.76  5013.5 2347.26  5016.7 2349.18
  5032.9 2351.23  5062.3 2350.18  5165.4 2358.05  5176.3 2357.77  5187.5 2359.55
  5331.2 2368.06  5341.5 2368.02  5386.4 2370.25  5398.2 2371.74  5489.4 2375.72
  5557.8 2377.79  5580.7 2379.05  5586.2 2380.20  5603.5 2380.29  5609.5 2381.14
#Mann=3,-1,0
  4548.2    0.07       0  5008.0    0.07       0  5013.5    0.07       0
Bank Sta=5008,5013.5
Exp/Cntr=0.3,0.1

Type RM Length L Ch R = 1,28109,162,162,162
BEGIN DESCRIPTION:
Little Elm Creek 2 28109.207
END DESCRIPTION:
XS GIS Cut Line= 3
      1497042.49      6762434.49      1497079.96      6761937.90
      1497138.84      6761408.46
#Sta/Elev= 30
  4502.0 2369.33  4538.6 2368.60  4568.7 2368.95  4638.9 2366.82  4709.1 2362.33
  4759.2 2360.78  4799.3 2358.33  4839.4 2354.57  4859.5 2348.70  4866.1 2347.36
  4879.6 2346.96  4899.6 2347.85  4959.8 2348.75  4997.4 2346.28  5007.1 2346.14
  5007.6 2345.64  5012.4 2345.64  5012.9 2346.14  5070.3 2348.67  5172.0 2350.02
  5201.1 2349.90  5231.3 2351.37  5331.9 2361.08  5357.2 2362.42  5402.4 2366.75
  5450.2 2370.01  5455.2 2372.23  5482.9 2373.34  5513.0 2375.49  5532.7 2378.80
#Mann=5,-1,0
  4502.0    0.07       0  5007.1    0.07       0  5012.9    0.07       0
  5172.0    0.16       0  5357.2    0.07       0
Bank Sta=5007.1,5012.9
Exp/Cntr=0.3,0.1

Type RM Length L Ch R = 1,27947,107,107,107
BEGIN DESCRIPTION:
Little Elm Creek 2 27946.59
END DESCRIPTION:
XS GIS Cut Line= 3
      1497349.78      6762512.67      1497227.38      6761892.85
      1497193.60      6761401.80
#Sta/Elev= 30
  4363.8 2368.05  4419.5 2365.75  4473.1 2362.22  4482.4 2361.49  4603.0 2354.39
  4619.5 2352.53  4755.9 2354.37  4786.5 2356.08  4829.8 2356.85  4881.1 2352.46
  4898.6 2348.17  4919.0 2344.82  4959.8 2345.92  4978.6 2344.40  4980.8 2342.92
  4981.3 2342.42  4986.6 2342.92  4990.3 2342.95  4995.5 2345.25  5030.5 2346.92
  5150.8 2348.77  5180.9 2351.13  5210.9 2355.82  5256.0 2359.60  5318.3 2365.44
  5381.3 2370.61  5395.5 2370.72  5401.4 2372.55  5421.4 2375.12  5487.8 2382.17
#Mann=7,-1,0
  4363.8    0.07       0  4473.1    0.16       0  4482.4    0.07       0
  4980.8    0.07       0  4986.6    0.07       0  5256.0    0.16       0
  5318.3    0.07       0
Bank Sta=4980.8,4986.6
Exp/Cntr=0.3,0.1

Type RM Length L Ch R = 1,27840,143,143,143
BEGIN DESCRIPTION:
Little Elm Creek 2 27839.56
END DESCRIPTION:
XS GIS Cut Line= 3
      1497448.73      6762510.02      1497334.15      6761887.64
      1497266.55      6761422.26
#Sta/Elev= 30
  4366.8 2369.05  4444.3 2365.85  4460.4 2364.49  4519.9 2362.54  4673.9 2353.54
  4690.2 2351.49  4755.2 2350.29  4785.7 2348.55  4795.9 2348.90  4826.4 2352.30
  4887.4 2351.86  4907.4 2349.74  4912.5 2350.06  4948.4 2345.79  4989.1 2343.52
  4994.0 2342.30  4994.5 2341.80  4999.8 2342.30  5019.5 2343.01  5031.6 2344.65
  5150.8 2347.33  5201.4 2350.18  5231.7 2354.59  5237.0 2356.28  5292.3 2362.20
  5322.6 2364.36  5352.9 2369.13  5433.8 2371.53  5447.4 2372.99  5469.9 2377.39
#Mann=5,-1,0
  4366.8    0.07       0  4444.3    0.16       0  4519.9    0.07       0
  4994.0    0.07       0  4999.8    0.07       0
Bank Sta=4994,4999.8
Exp/Cntr=0.3,0.1

Type RM Length L Ch R = 1,27697,152,152,152
BEGIN DESCRIPTION:
Little Elm Creek 2 27697.29
END DESCRIPTION:
XS GIS Cut Line= 3
      1497493.01      6762471.02      1497461.76      6761840.77
      1497303.00      6761382.73
#Sta/Elev= 30
  4377.5 2367.01  4399.5 2366.24  4514.8 2362.74  4618.3 2355.73  4664.1 2352.73
  4720.9 2349.01  4801.0 2346.52  4844.1 2347.00  4961.2 2343.98  4991.3 2344.37
  5011.2 2343.78  5012.4 2342.29  5012.9 2341.79  5018.2 2342.29  5032.6 2344.56
  5041.2 2343.81  5046.5 2344.66  5053.8 2343.83  5103.5 2343.86  5127.9 2345.28
  5159.6 2345.73  5191.4 2349.31  5233.7 2356.48  5285.0 2361.81  5316.2 2362.75
  5352.6 2365.40  5360.7 2366.97  5434.8 2371.40  5466.6 2375.38  5493.3 2380.16
#Mann=7,-1,0
  4377.5    0.07       0  4399.5    0.16       0  4514.8    0.07       0
  4618.3    0.16       0  4664.1    0.07       0  5012.4    0.07       0
  5018.2    0.07       0
Bank Sta=5012.4,5018.2
Exp/Cntr=0.3,0.1

Type RM Length L Ch R = 1,27545,130,130,130
BEGIN DESCRIPTION:
Little Elm Creek 2 27545.25
END DESCRIPTION:
XS GIS Cut Line= 3
      1497524.25      6762494.46      1497586.76      6761848.58
      1497753.41      6761405.91
#Sta/Elev= 30
  4341.0 2369.01  4377.0 2367.41  4503.9 2362.19  4638.8 2354.67  4663.3 2352.14
  4689.1 2349.86  4739.3 2349.18  4759.4 2346.21  4991.8 2342.54  5033.3 2342.82
  5104.8 2338.81  5105.3 2338.31  5110.6 2338.81  5113.0 2338.93  5129.4 2345.71
  5143.2 2347.60  5150.8 2350.10  5161.5 2351.73  5168.1 2354.38  5182.8 2357.10
  5283.6 2367.74  5308.5 2368.50  5385.9 2373.85  5393.8 2374.55  5399.2 2376.37
  5424.1 2376.90  5429.4 2379.00  5448.9 2380.16  5454.3 2382.93  5462.9 2383.66
#Mann=6,-1,0
  4341.0    0.07       0  4377.0    0.16       0  4663.3    0.07       0
  4991.8    0.16       0  5104.8    0.07       0  5110.6    0.16       0
Bank Sta=5104.8,5110.6
Exp/Cntr=0.3,0.1

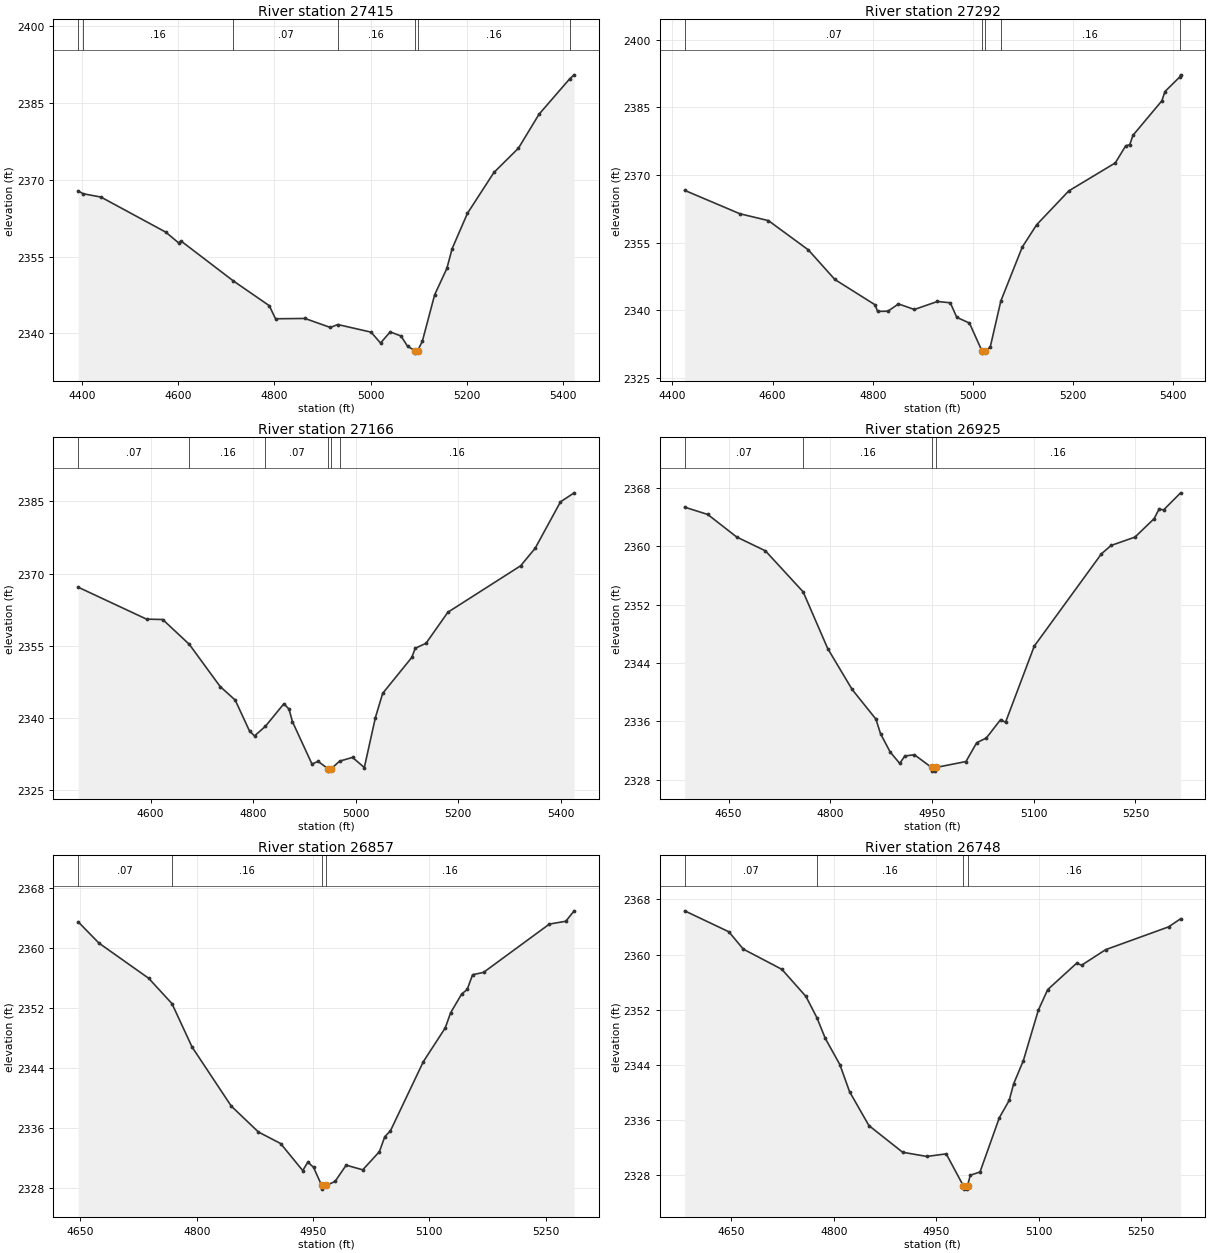
Type RM Length L Ch R = 1,27415,123,123,123
BEGIN DESCRIPTION:
Little Elm Creek 2 27414.84
END DESCRIPTION:
XS GIS Cut Line= 3
      1497545.08      6762473.61      1497703.94      6761890.25
      1497847.19      6761489.16
#Sta/Elev= 30
  4392.2 2367.80  4402.2 2367.26  4439.5 2366.60  4574.2 2359.76  4600.7 2357.68
  4605.8 2358.04  4714.4 2350.26  4789.1 2345.43  4802.2 2342.87  4863.4 2342.93
  4916.2 2341.17  4931.5 2341.75  5000.7 2340.26  5020.4 2338.14  5040.5 2340.31
  5062.9 2339.51  5076.6 2337.50  5091.8 2336.67  5092.3 2336.17  5097.7 2336.67
  5107.3 2338.50  5132.8 2347.54  5158.3 2352.71  5169.1 2356.53  5200.9 2363.42
  5256.0 2371.40  5307.0 2376.14  5349.6 2382.74  5413.3 2389.65  5422.7 2390.44
#Mann=7,-1,0
  4392.2    0.07       0  4402.2    0.16       0  4714.4    0.07       0
  4931.5    0.16       0  5091.8    0.07       0  5097.7    0.16       0
  5413.3    0.07       0
Bank Sta=5091.8,5097.7
Exp/Cntr=0.3,0.1

Type RM Length L Ch R = 1,27292,126,126,126
BEGIN DESCRIPTION:
Little Elm Creek 2 27291.89
END DESCRIPTION:
XS GIS Cut Line= 3
      1497615.41      6762481.37      1497800.30      6761947.54
      1498132.95      6761682.45
#Sta/Elev= 30
  4424.5 2366.58  4534.7 2361.39  4591.7 2359.87  4671.5 2353.37  4724.4 2346.81
  4804.5 2341.21  4809.8 2339.74  4830.2 2339.77  4851.4 2341.39  4883.1 2340.16
  4929.1 2341.93  4954.9 2341.65  4967.8 2338.42  4993.1 2337.15  5018.1 2330.98
  5018.5 2330.48  5024.0 2330.98  5034.5 2331.76  5055.8 2342.04  5098.6 2354.00
  5127.4 2358.96  5191.5 2366.46  5284.4 2372.67  5305.2 2376.47  5313.2 2376.70
  5319.6 2378.78  5377.2 2386.42  5383.6 2388.50  5412.8 2391.70  5414.8 2392.20
#Mann=5,-1,0
  4424.5    0.07       0  5018.1    0.07       0  5024.0    0.07       0
  5055.8    0.16       0  5412.8    0.07       0
Bank Sta=5018.1,5024
Exp/Cntr=0.3,0.1

Type RM Length L Ch R = 1,27166,241,241,241
BEGIN DESCRIPTION:
Little Elm Creek 2 27166.47
END DESCRIPTION:
XS GIS Cut Line= 3
      1497651.84      6762515.27      1497896.65      6762028.27
      1498209.12      6761744.44
#Sta/Elev= 30
  4458.7 2367.18  4591.9 2360.55  4623.5 2360.47  4675.3 2355.32  4735.5 2346.55
  4764.9 2343.73  4792.8 2337.30  4802.6 2336.29  4823.9 2338.30  4859.8 2342.97
  4869.8 2341.86  4876.5 2339.25  4914.5 2330.46  4926.7 2330.98  4946.0 2329.47
  4946.5 2328.97  4952.1 2329.47  4968.6 2331.05  4993.7 2331.82  5016.7 2329.72
  5038.3 2340.11  5052.5 2345.13  5109.3 2352.60  5116.0 2354.50  5137.0 2355.53
  5179.6 2361.98  5321.5 2371.63  5349.9 2375.28  5399.2 2384.91  5425.9 2386.79
#Mann=6,-1,0
  4458.7    0.07       0  4675.3    0.16       0  4823.9    0.07       0
  4946.0    0.07       0  4952.1    0.07       0  4968.6    0.16       0
Bank Sta=4946,4952.1
Exp/Cntr=0.3,0.1

Type RM Length L Ch R = 1,26925,68,68,68
BEGIN DESCRIPTION:
Little Elm Creek 2 26925.34
END DESCRIPTION:
XS GIS Cut Line= 3
      1497701.33      6762512.65      1498008.63      6762234.00
      1498234.99      6762012.84
#Sta/Elev= 30
  4585.3 2365.40  4619.3 2364.40  4661.9 2361.31  4704.4 2359.40  4760.0 2353.77
  4796.3 2345.97  4832.2 2340.37  4867.3 2336.29  4874.1 2334.29  4888.3 2331.78
  4902.4 2330.21  4909.9 2331.23  4924.1 2331.40  4949.4 2329.65  4949.9 2329.15
  4955.1 2329.15  4955.6 2329.65  5000.1 2330.47  5015.9 2333.05  5030.1 2333.70
  5051.2 2336.23  5058.4 2335.85  5100.8 2346.32  5199.8 2358.99  5214.0 2360.14
  5249.3 2361.29  5277.5 2363.82  5284.7 2365.11  5291.7 2365.04  5316.6 2367.37
#Mann=4,-1,0
  4585.3    0.07       0  4760.0    0.16       0  4949.4    0.07       0
  4955.6    0.16       0
Bank Sta=4949.4,4955.6
Exp/Cntr=0.3,0.1

Type RM Length L Ch R = 1,26857,109,109,109
BEGIN DESCRIPTION:
Little Elm Creek 2 26857.05
END DESCRIPTION:
XS GIS Cut Line= 3
      1497784.66      6762515.25      1498058.11      6762280.87
      1498250.38      6762078.21
#Sta/Elev= 30
  4647.2 2363.45  4674.0 2360.62  4738.1 2355.94  4768.1 2352.57  4794.0 2346.80
  4844.5 2338.94  4879.6 2335.48  4908.2 2333.95  4936.7 2330.35  4943.3 2331.47
  4950.6 2330.79  4961.1 2328.38  4961.6 2327.88  4967.3 2328.38  4978.4 2328.90
  4992.7 2331.07  5014.1 2330.45  5035.6 2332.87  5042.5 2334.86  5049.7 2335.62
  5092.2 2344.84  5120.5 2349.34  5127.4 2351.35  5141.6 2353.84  5148.8 2354.46
  5155.7 2356.41  5169.9 2356.73  5254.8 2363.16  5275.9 2363.53  5286.7 2364.92
#Mann=4,-1,0
  4647.2    0.07       0  4768.1    0.16       0  4961.1    0.07       0
  4967.3    0.16       0
Bank Sta=4961.1,4967.3
Exp/Cntr=0.3,0.1

Type RM Length L Ch R = 1,26748,149,149,149
BEGIN DESCRIPTION:
Little Elm Creek 2 26747.8
END DESCRIPTION:
XS GIS Cut Line= 3
      1497841.98      6762666.27      1498131.03      6762361.60
      1498361.41      6762159.69
#Sta/Elev= 30
  4581.5 2366.34  4646.2 2363.30  4667.3 2360.79  4723.9 2357.85  4759.1 2353.92
  4775.2 2350.83  4787.4 2347.84  4808.8 2344.03  4823.0 2340.10  4851.3 2335.19
  4900.7 2331.32  4936.2 2330.71  4964.5 2331.09  4989.5 2326.47  4990.0 2325.97
  4995.2 2325.97  4995.7 2326.47  4999.8 2327.99  5014.0 2328.46  5042.4 2336.35
  5056.7 2338.83  5063.3 2341.25  5077.5 2344.62  5099.4 2351.92  5113.1 2354.91
  5155.4 2358.73  5162.9 2358.46  5198.1 2360.71  5290.1 2364.01  5307.8 2365.19
#Mann=4,-1,0
  4581.5    0.07       0  4775.2    0.16       0  4989.5    0.07       0
  4995.7    0.16       0
Bank Sta=4989.5,4995.7
Exp/Cntr=0.3,0.1

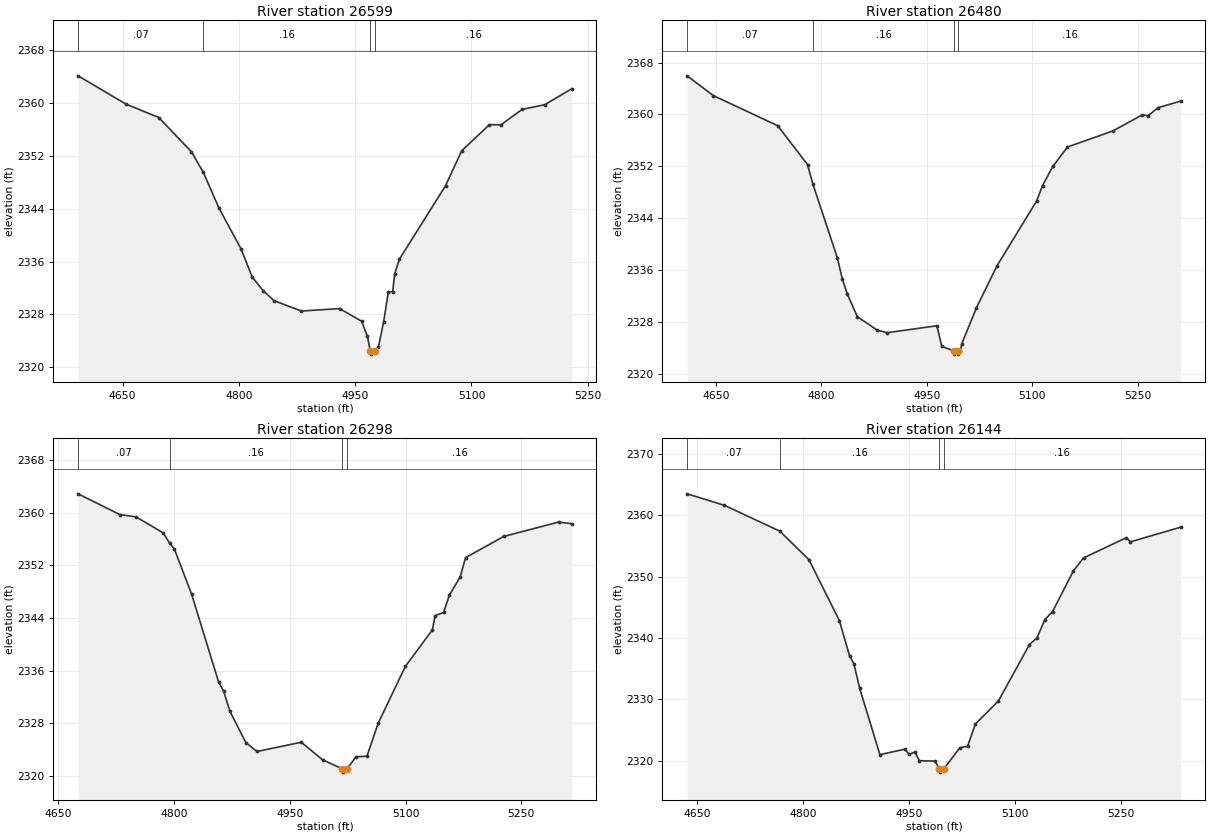
Type RM Length L Ch R = 1,26599,119,119,119
BEGIN DESCRIPTION:
Little Elm Creek 2 26599.08
END DESCRIPTION:
XS GIS Cut Line= 3
      1497946.14      6762715.76      1498248.21      6762444.93
      1498380.51      6762255.57
#Sta/Elev= 30
  4592.6 2364.09  4654.1 2359.83  4696.7 2357.78  4738.8 2352.60  4754.2 2349.47
  4774.4 2344.06  4802.8 2337.91  4817.1 2333.68  4831.3 2331.58  4845.5 2330.07
  4880.6 2328.51  4929.9 2328.88  4958.3 2326.97  4965.8 2324.66  4969.4 2322.49
  4969.9 2321.99  4975.6 2322.49  4980.0 2323.07  4986.7 2326.89  4992.8 2331.41
  4998.3 2331.41  5001.0 2334.16  5007.1 2336.37  5066.5 2347.46  5087.4 2352.76
  5123.1 2356.70  5138.0 2356.68  5165.3 2359.01  5194.7 2359.73  5229.3 2362.14
#Mann=4,-1,0
  4592.6    0.07       0  4754.2    0.16       0  4969.4    0.07       0
  4975.6    0.16       0
Bank Sta=4969.4,4975.6
Exp/Cntr=0.3,0.1

Type RM Length L Ch R = 1,26480,182,182,182
BEGIN DESCRIPTION:
Little Elm Creek 2 26479.51
END DESCRIPTION:
XS GIS Cut Line= 3
      1498039.91      6762825.11      1498308.11      6762543.89
      1498494.95      6762292.17
#Sta/Elev= 30
  4609.0 2365.95  4646.1 2362.92  4737.9 2358.27  4780.4 2352.27  4788.1 2349.22
  4822.8 2337.89  4829.7 2334.70  4837.0 2332.33  4851.1 2328.87  4879.5 2326.79
  4893.6 2326.40  4964.3 2327.47  4971.3 2324.28  4988.6 2323.60  4989.1 2323.10
  4994.3 2323.10  4994.8 2323.60  4997.6 2323.60  4999.8 2324.73  5020.6 2330.26
  5049.8 2336.71  5106.1 2346.67  5114.5 2349.06  5129.1 2351.99  5150.0 2354.99
  5214.7 2357.47  5256.4 2359.94  5264.7 2359.81  5278.9 2361.05  5311.1 2362.06
#Mann=4,-1,0
  4609.0    0.07       0  4788.1    0.16       0  4988.6    0.07       0
  4994.8    0.16       0
Bank Sta=4988.6,4994.8
Exp/Cntr=0.3,0.1

Type RM Length L Ch R = 1,26298,154,154,154
BEGIN DESCRIPTION:
Little Elm Creek 2 26298.03
END DESCRIPTION:
XS GIS Cut Line= 3
      1498235.18      6762924.11      1498524.26      6762561.97
      1498640.44      6762429.19
#Sta/Elev= 30
  4675.6 2362.89  4729.8 2359.73  4750.6 2359.39  4785.8 2356.96  4794.5 2355.35
  4800.2 2354.54  4822.7 2347.64  4857.9 2334.20  4864.3 2332.84  4872.3 2329.82
  4893.1 2325.03  4907.5 2323.69  4964.9 2325.10  4992.4 2322.43  5018.1 2321.05
  5018.6 2320.55  5024.4 2321.05  5035.6 2322.89  5050.0 2322.97  5064.5 2327.98
  5099.7 2336.63  5134.9 2342.21  5138.3 2344.36  5149.3 2344.84  5156.9 2347.50
  5170.8 2350.25  5177.8 2353.18  5227.1 2356.40  5298.3 2358.59  5315.4 2358.34
#Mann=4,-1,0
  4675.6    0.07       0  4794.5    0.16       0  5018.1    0.07       0
  5024.4    0.16       0
Bank Sta=5018.1,5024.4
Exp/Cntr=0.3,0.1

Type RM Length L Ch R = 1,26144,175,175,175
BEGIN DESCRIPTION:
Little Elm Creek 2 26144.43
END DESCRIPTION:
XS GIS Cut Line= 3
      1498334.15      6763030.87      1498563.32      6762749.62
      1498701.36      6762442.29
#Sta/Elev= 30
  4635.3 2363.52  4688.1 2361.65  4766.6 2357.44  4808.0 2352.78  4851.1 2342.85
  4865.5 2337.12  4871.9 2335.74  4879.8 2331.83  4908.6 2320.96  4943.7 2321.85
  4950.2 2321.01  4958.1 2321.40  4964.6 2319.97  4986.8 2319.91  4992.8 2318.61
  4993.3 2318.11  4999.1 2318.61  5021.8 2322.08  5032.8 2322.32  5044.0 2325.98
  5076.6 2329.73  5120.5 2338.92  5131.2 2340.01  5142.4 2343.00  5153.3 2344.31
  5183.0 2350.97  5197.2 2353.06  5258.0 2356.37  5263.5 2355.68  5335.0 2358.08
#Mann=4,-1,0
  4635.3    0.07       0  4766.6    0.16       0  4992.8    0.07       0
  4999.1    0.16       0
Bank Sta=4992.8,4999.1
Exp/Cntr=0.3,0.1