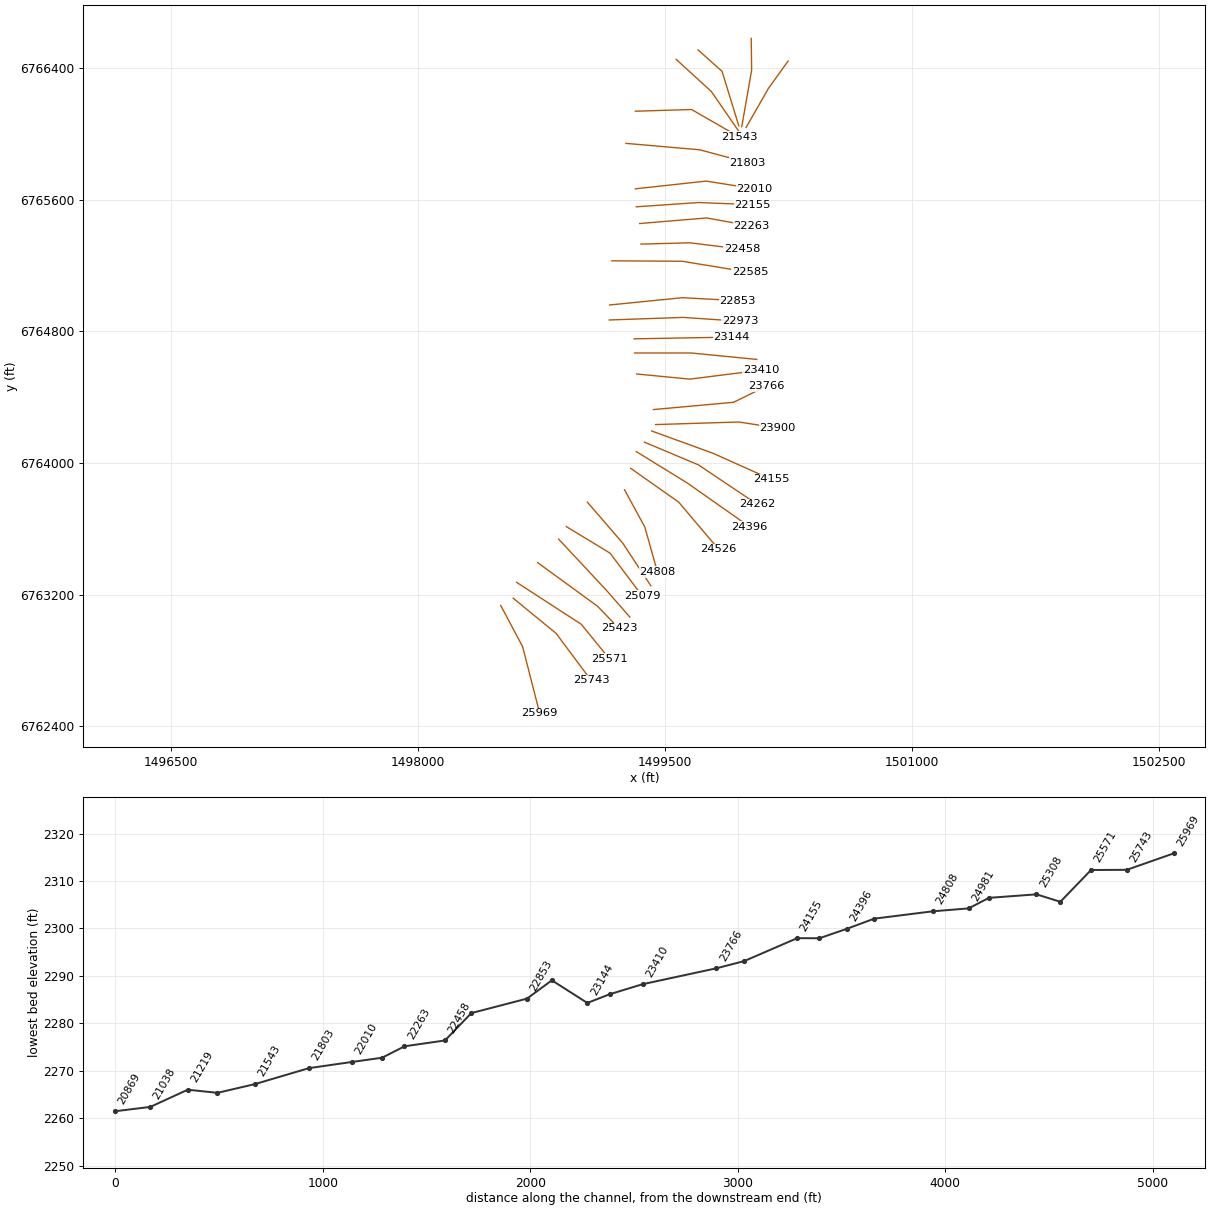
HEC-RAS study Little Elm Creek 2.prj: Little Elm Creek 2 Base Level Engineering

--- Little Elm Creek 2.g01 (geometry) --- (continued)

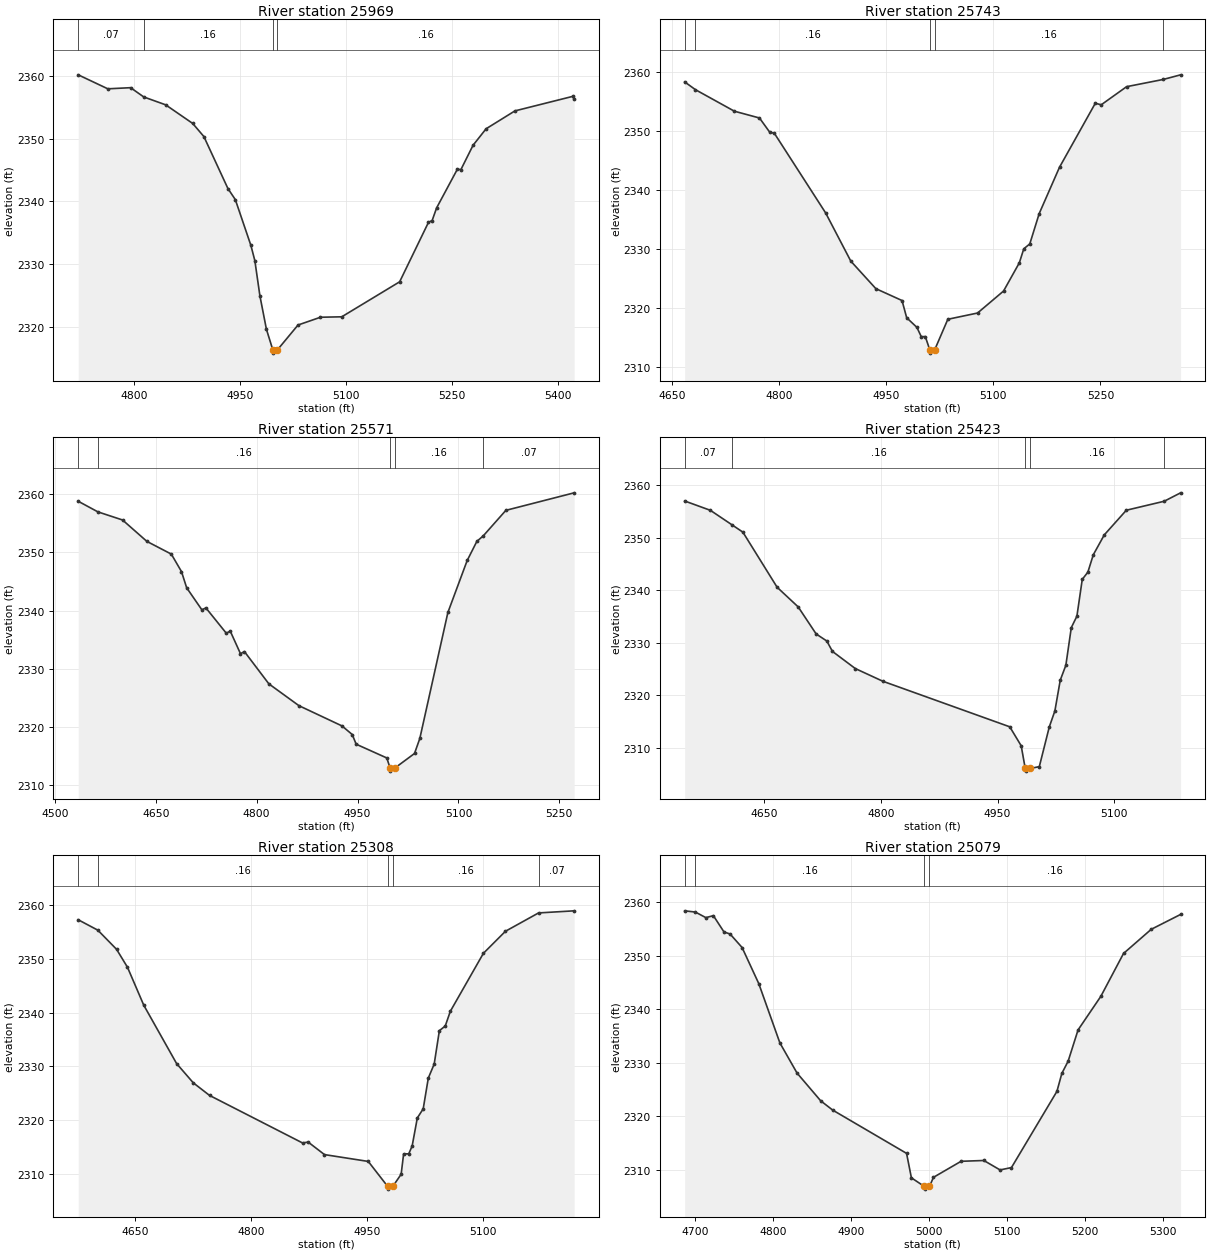
Type RM Length L Ch R = 1,25969,226,226,226
BEGIN DESCRIPTION:
Little Elm Creek 2 25969.25
END DESCRIPTION:
XS GIS Cut Line= 3
      1498503.43      6763135.02      1498636.23      6762885.04
      1498740.21      6762479.53
#Sta/Elev= 30
  4721.0 2360.18  4762.9 2357.95  4795.1 2358.13  4813.8 2356.65  4844.7 2355.40
  4883.0 2352.43  4898.8 2350.34  4932.8 2342.06  4943.3 2340.29  4965.3 2333.00
  4970.9 2330.57  4978.1 2324.94  4987.3 2319.62  4996.4 2316.32  4996.9 2315.82
  5002.7 2316.32  5032.0 2320.30  5063.8 2321.54  5093.9 2321.61  5175.8 2327.19
  5216.6 2336.67  5221.8 2336.96  5228.1 2338.97  5257.4 2345.12  5262.5 2345.08
  5279.7 2348.96  5298.1 2351.58  5338.9 2354.43  5420.5 2356.74  5422.7 2356.28
#Mann=4,-1,0
  4721.0    0.07       0  4813.8    0.16       0  4996.4    0.07       0
  5002.7    0.16       0
Bank Sta=4996.4,5002.7
Exp/Cntr=0.3,0.1

Type RM Length L Ch R = 1,25743,172,172,172
BEGIN DESCRIPTION:
Little Elm Creek 2 25742.77
END DESCRIPTION:
XS GIS Cut Line= 3
      1498578.92      6763179.33      1498839.36      6762965.77
      1499052.90      6762679.31
#Sta/Elev= 30
  4668.1 2358.35  4683.2 2357.03  4737.7 2353.38  4772.8 2352.23  4787.2 2349.81
  4793.6 2349.64  4865.4 2336.13  4900.6 2327.96  4935.7 2323.29  4972.3 2321.28
  4978.8 2318.36  4993.1 2316.73  4999.2 2315.16  5004.9 2315.16  5011.3 2312.86
  5011.8 2312.36  5017.8 2312.86  5036.4 2318.10  5078.0 2319.16  5114.4 2322.89
  5136.5 2327.68  5142.7 2330.05  5151.1 2330.88  5164.3 2336.03  5192.7 2343.88
  5242.8 2354.73  5251.1 2354.47  5286.6 2357.54  5338.0 2358.77  5362.2 2359.55
#Mann=5,-1,0
  4668.1    0.07       0  4683.2    0.16       0  5011.3    0.07       0
  5017.8    0.16       0  5338.0    0.07       0
Bank Sta=5011.3,5017.8
Exp/Cntr=0.3,0.1

Type RM Length L Ch R = 1,25571,148,148,148
BEGIN DESCRIPTION:
Little Elm Creek 2 25571.4
END DESCRIPTION:
XS GIS Cut Line= 3
      1498599.80      6763275.64      1498993.01      6763020.45
      1499162.29      6762812.11
#Sta/Elev= 30
  4534.8 2358.83  4564.0 2357.00  4600.7 2355.60  4636.9 2351.91  4673.2 2349.72
  4688.3 2346.71  4696.0 2343.92  4718.6 2340.12  4724.6 2340.45  4754.9 2336.09
  4760.8 2336.45  4776.0 2332.56  4781.9 2332.92  4818.2 2327.36  4862.9 2323.60
  4926.9 2320.11  4942.1 2318.63  4948.0 2316.96  4993.5 2314.59  4998.5 2312.82
  4999.0 2312.32  5005.1 2312.82  5034.7 2315.36  5042.6 2317.95  5084.3 2339.66
  5113.0 2348.62  5127.4 2351.92  5136.8 2352.85  5170.5 2357.26  5272.0 2360.28
#Mann=5,-1,0
  4534.8    0.07       0  4564.0    0.16       0  4998.5    0.07       0
  5005.1    0.16       0  5136.8    0.07       0
Bank Sta=4998.5,5005.1
Exp/Cntr=0.3,0.1

Type RM Length L Ch R = 1,25423,115,115,115
BEGIN DESCRIPTION:
Little Elm Creek 2 25423.2
END DESCRIPTION:
XS GIS Cut Line= 3
      1498727.37      6763395.46      1499091.96      6763129.83
      1499221.09      6762995.53
#Sta/Elev= 30
  4547.8 2356.95  4580.9 2355.17  4608.2 2352.46  4622.6 2351.03  4666.6 2340.56
  4693.7 2336.82  4716.8 2331.68  4730.5 2330.34  4737.7 2328.37  4767.1 2325.11
  4802.6 2322.69  4965.6 2314.04  4980.3 2310.44  4985.5 2306.12  4986.0 2305.62
  4992.1 2306.12  5003.6 2306.48  5016.4 2314.01  5023.6 2317.06  5030.5 2322.90
  5037.7 2325.73  5044.7 2332.89  5051.9 2335.06  5058.8 2342.06  5066.0 2343.43
  5073.0 2346.74  5087.1 2350.51  5115.4 2355.19  5164.1 2356.90  5185.2 2358.50
#Mann=5,-1,0
  4547.8    0.07       0  4608.2    0.16       0  4985.5    0.07       0
  4992.1    0.16       0  5164.1    0.07       0
Bank Sta=4985.5,4992.1
Exp/Cntr=0.3,0.1

Type RM Length L Ch R = 1,25308,229,229,229
BEGIN DESCRIPTION:
Little Elm Creek 2 25307.699
END DESCRIPTION:
XS GIS Cut Line= 3
      1498855.01      6763537.99      1499144.21      6763228.33
      1499287.25      6763064.75
#Sta/Elev= 30
  4576.3 2357.28  4601.7 2355.34  4625.9 2351.78  4640.0 2348.44  4661.0 2341.40
  4703.5 2330.53  4725.0 2326.96  4746.0 2324.62  4866.2 2315.78  4873.5 2315.94
  4894.6 2313.61  4951.2 2312.34  4976.3 2307.69  4976.8 2307.19  4982.9 2307.69
  4993.7 2309.96  4996.9 2313.75  5003.5 2313.75  5007.9 2315.20  5014.6 2320.43
  5022.2 2322.12  5028.8 2327.84  5036.4 2330.44  5043.1 2336.66  5050.7 2337.52
  5057.3 2340.27  5100.0 2351.04  5128.5 2355.14  5171.3 2358.55  5217.3 2358.94
#Mann=5,-1,0
  4576.3    0.07       0  4601.7    0.16       0  4976.3    0.07       0
  4982.9    0.16       0  5171.3    0.07       0
Bank Sta=4976.3,4982.9
Exp/Cntr=0.3,0.1

Type RM Length L Ch R = 1,25079,98,98,98
BEGIN DESCRIPTION:
Little Elm Creek 2 25078.98
END DESCRIPTION:
XS GIS Cut Line= 3
      1498901.90      6763614.18      1499167.48      6763452.75
      1499362.55      6763192.66
#Sta/Elev= 30
  4687.1 2358.35  4700.8 2358.12  4714.3 2357.08  4723.9 2357.45  4737.5 2354.41
  4745.3 2354.03  4760.7 2351.51  4782.1 2344.78  4809.2 2333.71  4831.2 2328.09
  4861.5 2322.92  4877.0 2321.18  4971.6 2313.12  4977.8 2308.56  4994.4 2306.95
  4994.9 2306.45  5001.0 2306.95  5006.1 2308.65  5041.5 2311.64  5070.7 2311.79
  5091.5 2310.03  5106.1 2310.47  5164.4 2324.68  5170.7 2328.03  5178.8 2330.32
  5191.5 2336.14  5220.7 2342.40  5249.8 2350.40  5285.3 2354.90  5323.0 2357.68
#Mann=4,-1,0
  4687.1    0.07       0  4700.8    0.16       0  4994.4    0.07       0
  5001.0    0.16       0
Bank Sta=4994.4,5001
Exp/Cntr=0.3,0.1

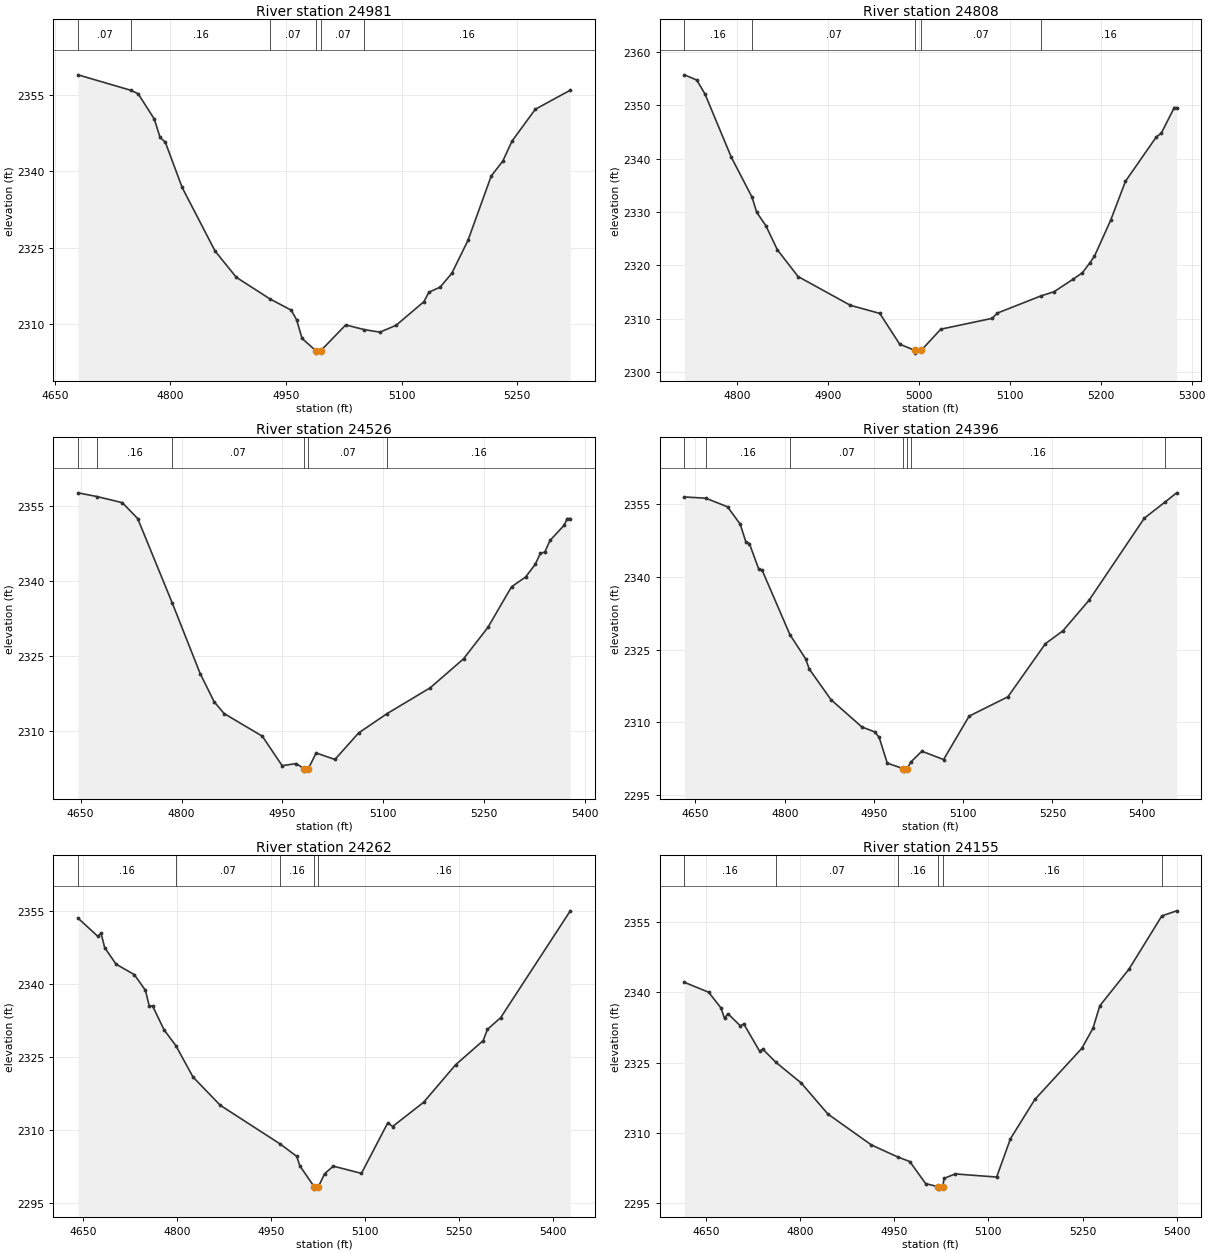
Type RM Length L Ch R = 1,24981,173,173,173
BEGIN DESCRIPTION:
Little Elm Creek 2 24980.58
END DESCRIPTION:
XS GIS Cut Line= 3
      1499029.48      6763762.62      1499243.01      6763515.25
      1499414.88      6763254.83
#Sta/Elev= 30
  4680.2 2358.99  4748.6 2355.95  4758.2 2355.27  4779.1 2350.31  4786.7 2346.66
  4793.4 2345.77  4815.3 2336.83  4858.0 2324.33  4885.5 2319.16  4929.4 2314.88
  4956.8 2312.69  4963.7 2310.83  4971.0 2307.11  4988.6 2304.73  4989.1 2304.23
  4995.3 2304.73  5027.6 2309.78  5051.5 2308.86  5071.9 2308.36  5092.9 2309.70
  5129.0 2314.35  5135.5 2316.21  5150.1 2317.22  5165.2 2319.93  5186.2 2326.41
  5216.4 2339.09  5231.3 2341.99  5243.4 2345.96  5273.6 2352.22  5319.0 2355.97
#Mann=6,-1,0
  4680.2    0.07       0  4748.6    0.16       0  4929.4    0.07       0
  4988.6    0.07       0  4995.3    0.07       0  5051.5    0.16       0
Bank Sta=4988.6,4995.3
Exp/Cntr=0.3,0.1

Type RM Length L Ch R = 1,24808,282,282,282
BEGIN DESCRIPTION:
Little Elm Creek 2 24808.168
END DESCRIPTION:
XS GIS Cut Line= 3
      1499255.01      6763837.98      1499378.51      6763611.00
      1499455.00      6763338.01
#Sta/Elev= 30
  4741.6 2355.66  4755.3 2354.68  4764.3 2352.07  4793.3 2340.24  4816.0 2332.81
  4821.3 2329.93  4831.3 2327.45  4844.0 2322.93  4866.8 2317.93  4924.4 2312.55
  4956.7 2311.04  4978.6 2305.29  4995.5 2304.11  4996.0 2303.61  5002.2 2304.11
  5023.9 2308.09  5080.3 2310.11  5086.2 2311.10  5133.8 2314.29  5148.5 2315.09
  5169.3 2317.41  5179.7 2318.63  5187.8 2320.46  5193.0 2321.73  5210.8 2328.43
  5227.2 2335.76  5261.3 2344.09  5266.5 2344.71  5280.9 2349.54  5283.5 2349.54
#Mann=5,-1,0
  4741.6    0.16       0  4816.0    0.07       0  4995.5    0.07       0
  5002.2    0.07       0  5133.8    0.16       0
Bank Sta=4995.5,5002.2
Exp/Cntr=0.3,0.1

Type RM Length L Ch R = 1,24526,130,130,130
BEGIN DESCRIPTION:
Little Elm Creek 2 24526.04
END DESCRIPTION:
XS GIS Cut Line= 3
      1499292.51      6763968.35      1499584.15      6763762.64
      1499826.33      6763476.19
#Sta/Elev= 30
  4646.1 2357.63  4674.2 2356.89  4711.9 2355.67  4734.8 2352.50  4786.4 2335.57
  4827.7 2321.55  4848.6 2315.89  4863.4 2313.55  4920.1 2309.04  4949.6 2303.15
  4970.6 2303.57  4981.9 2302.56  4982.4 2302.06  4988.7 2302.56  5000.1 2305.69
  5028.1 2304.39  5063.3 2309.68  5105.3 2313.52  5169.8 2318.70  5219.3 2324.48
  5255.6 2330.76  5290.7 2338.87  5311.6 2340.82  5325.9 2343.34  5333.6 2345.55
  5340.2 2345.81  5347.9 2348.12  5368.7 2351.12  5373.6 2352.50  5378.1 2352.50
#Mann=6,-1,0
  4646.1    0.07       0  4674.2    0.16       0  4786.4    0.07       0
  4981.9    0.07       0  4988.7    0.07       0  5105.3    0.16       0
Bank Sta=4981.9,4988.7
Exp/Cntr=0.3,0.1

Type RM Length L Ch R = 1,24396,134,134,134
BEGIN DESCRIPTION:
Little Elm Creek 2 24396.26
END DESCRIPTION:
XS GIS Cut Line= 3
      1499326.31      6764069.95      1499638.84      6763877.23
      1500015.43      6763612.32
#Sta/Elev= 30
  4631.3 2356.54  4667.3 2356.28  4703.9 2354.50  4725.2 2350.92  4734.7 2347.24
  4740.6 2346.92  4756.0 2341.76  4761.9 2341.46  4808.8 2328.11  4835.2 2323.13
  4841.2 2321.03  4877.8 2314.70  4929.8 2309.06  4951.1 2308.06  4958.7 2306.95
  4972.4 2301.60  4999.5 2300.45  5000.0 2299.95  5006.3 2300.45  5011.5 2301.77
  5030.5 2304.06  5067.1 2302.34  5110.0 2311.30  5175.3 2315.30  5238.3 2326.26
  5267.7 2328.91  5311.7 2335.23  5404.5 2352.15  5439.8 2355.53  5458.9 2357.39
#Mann=7,-1,0
  4631.3    0.07       0  4667.3    0.16       0  4808.8    0.07       0
  4999.5    0.07       0  5006.3    0.07       0  5011.5    0.16       0
  5439.8    0.07       0
Bank Sta=4999.5,5006.3
Exp/Cntr=0.3,0.1

Type RM Length L Ch R = 1,24262,107,107,107
BEGIN DESCRIPTION:
Little Elm Creek 2 24261.78
END DESCRIPTION:
XS GIS Cut Line= 3
      1499375.85      6764127.21      1499703.94      6763989.20
      1500060.39      6763749.84
#Sta/Elev= 30
  4641.7 2353.45  4673.1 2349.75  4678.5 2350.34  4684.2 2347.42  4702.3 2344.03
  4731.5 2341.88  4749.3 2338.65  4755.2 2335.48  4760.6 2335.47  4778.9 2330.58
  4797.9 2327.30  4825.2 2320.89  4868.6 2315.11  4964.4 2307.16  4990.6 2304.64
  4995.5 2302.71  5018.4 2298.43  5018.9 2297.93  5025.2 2298.43  5035.0 2301.08
  5048.9 2302.64  5093.8 2301.16  5135.9 2311.53  5143.5 2310.76  5192.9 2315.71
  5243.9 2323.39  5288.0 2328.36  5294.9 2330.68  5315.9 2333.06  5427.0 2354.95
#Mann=5,-1,0
  4641.7    0.16       0  4797.9    0.07       0  4964.4    0.16       0
  5018.4    0.07       0  5025.2    0.16       0
Bank Sta=5018.4,5025.2
Exp/Cntr=0.3,0.1

Type RM Length L Ch R = 1,24155,255,255,255
BEGIN DESCRIPTION:
Little Elm Creek 2 24154.88
END DESCRIPTION:
XS GIS Cut Line= 3
      1499420.09      6764194.93      1499792.48      6764059.52
      1500146.64      6763900.67
#Sta/Elev= 30
  4615.5 2342.14  4654.2 2340.02  4673.9 2336.65  4679.5 2334.42  4684.8 2335.45
  4704.7 2332.83  4710.1 2333.26  4735.3 2327.45  4740.6 2327.84  4761.0 2325.09
  4801.8 2320.61  4844.2 2314.00  4913.6 2307.38  4955.4 2304.83  4974.7 2303.84
  5000.0 2299.13  5020.4 2298.45  5020.9 2297.95  5027.2 2298.45  5029.3 2300.24
  5047.0 2301.20  5113.1 2300.53  5135.1 2308.72  5173.9 2317.10  5248.9 2328.05
  5266.6 2332.33  5277.5 2337.13  5323.9 2344.94  5376.3 2356.32  5399.9 2357.41
#Mann=6,-1,0
  4615.5    0.16       0  4761.0    0.07       0  4955.4    0.16       0
  5020.4    0.07       0  5027.2    0.16       0  5376.3    0.07       0
Bank Sta=5020.4,5027.2
Exp/Cntr=0.3,0.1

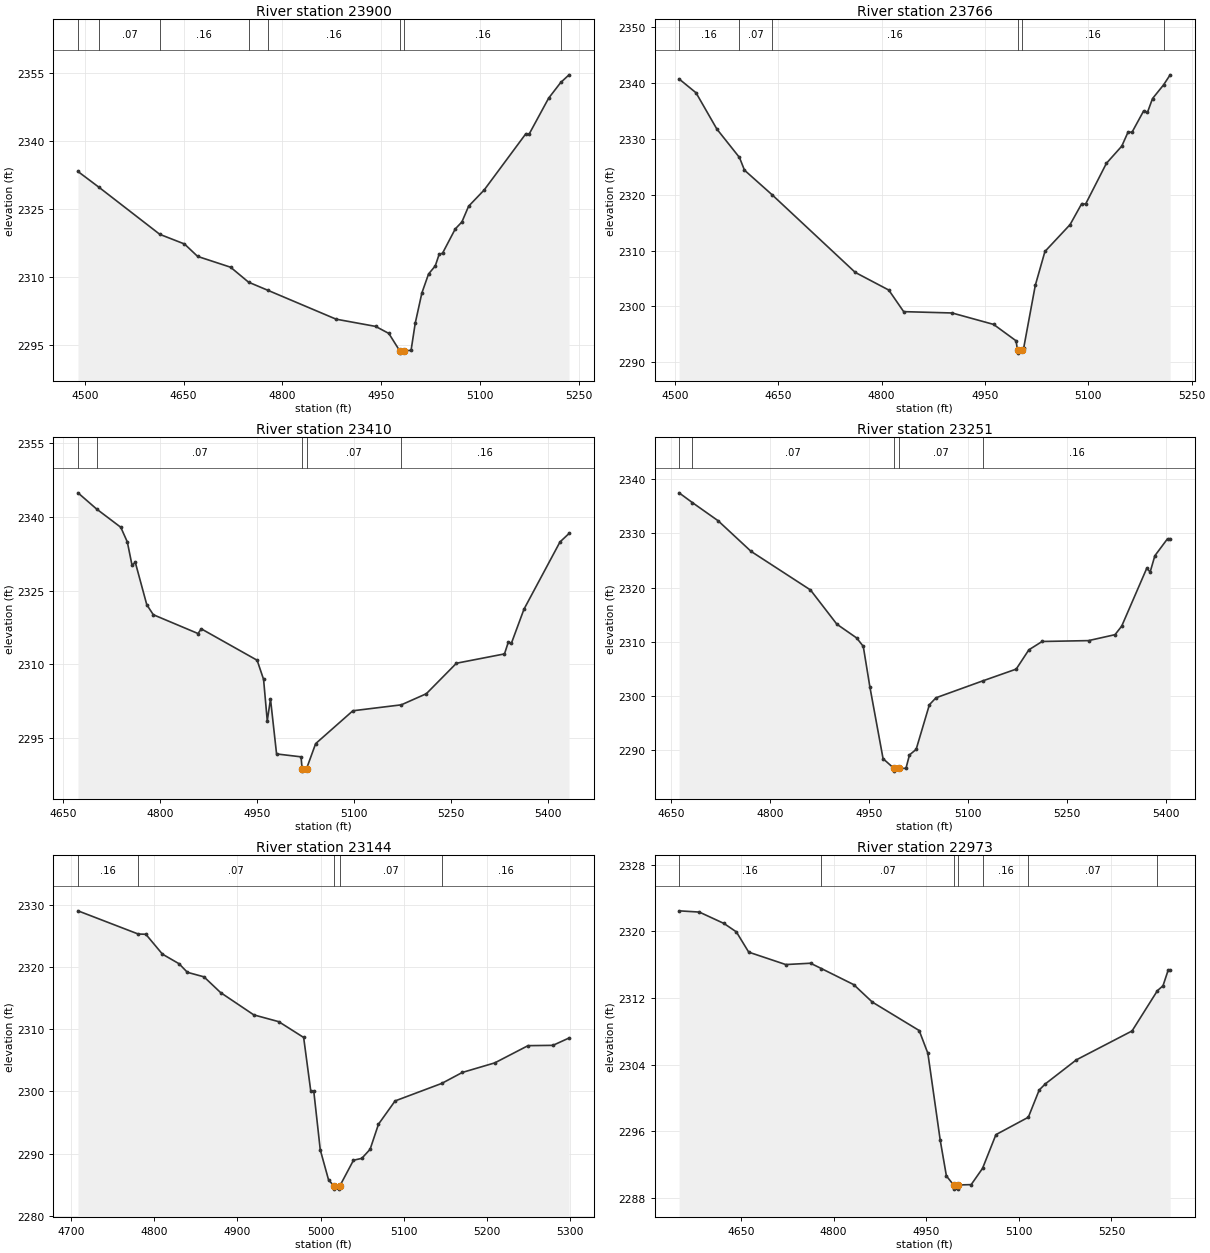
Type RM Length L Ch R = 1,23900,134,134,134
BEGIN DESCRIPTION:
Little Elm Creek 2 23900.33
END DESCRIPTION:
XS GIS Cut Line= 3
      1499443.50      6764234.00      1499948.73      6764249.62
      1500185.67      6764213.17
#Sta/Elev= 30
  4489.8 2333.29  4521.7 2329.80  4614.0 2319.39  4651.4 2317.26  4671.4 2314.51
  4721.4 2312.12  4748.7 2308.81  4778.4 2306.99  4881.5 2300.63  4941.5 2299.03
  4961.5 2297.48  4978.1 2293.62  4978.6 2293.12  4984.9 2293.62  4995.3 2293.74
  5001.6 2299.75  5011.7 2306.43  5021.8 2310.62  5032.0 2312.41  5037.9 2314.98
  5043.0 2315.21  5062.3 2320.58  5072.4 2322.13  5082.6 2325.61  5106.2 2329.20
  5169.5 2341.65  5174.5 2341.58  5204.0 2349.50  5222.4 2352.98  5235.0 2354.67
#Mann=8,-1,0
  4489.8    0.16       0  4521.7    0.07       0  4614.0    0.16       0
  4748.7    0.07       0  4778.4    0.16       0  4978.1    0.07       0
  4984.9    0.16       0  5222.4    0.07       0
Bank Sta=4978.1,4984.9
Exp/Cntr=0.3,0.1

Type RM Length L Ch R = 1,23766,356,356,356
BEGIN DESCRIPTION:
Little Elm Creek 2 23766.12
END DESCRIPTION:
XS GIS Cut Line= 3
      1499430.46      6764325.14      1499917.48      6764369.41
      1500117.97      6764468.35
#Sta/Elev= 30
  4506.1 2340.77  4530.7 2338.29  4560.9 2331.79  4593.7 2326.69  4601.0 2324.41
  4641.0 2320.01  4761.7 2306.08  4810.4 2302.91  4832.0 2299.04  4902.3 2298.80
  4962.5 2296.75  4995.1 2293.81  4997.2 2292.10  4997.7 2291.60  5004.0 2292.10
  5006.2 2292.53  5023.0 2303.75  5037.0 2309.83  5073.5 2314.65  5090.4 2318.41
  5096.0 2318.33  5126.2 2325.64  5148.5 2328.72  5157.7 2331.27  5163.3 2331.20
  5180.2 2335.03  5185.8 2334.78  5193.1 2337.25  5209.1 2339.70  5218.7 2341.51
#Mann=6,-1,0
  4506.1    0.16       0  4593.7    0.07       0  4641.0    0.16       0
  4997.2    0.07       0  5004.0    0.16       0  5209.1    0.07       0
Bank Sta=4997.2,5004
Exp/Cntr=0.3,0.1

Type RM Length L Ch R = 1,23410,159,159,159
BEGIN DESCRIPTION:
Little Elm Creek 2 23409.87
END DESCRIPTION:
XS GIS Cut Line= 3
      1499328.99      6764541.28      1499651.86      6764510.04
      1500084.13      6764564.72
#Sta/Elev= 30
  4673.2 2344.91  4702.0 2341.62  4739.5 2337.89  4749.6 2334.90  4756.9 2330.15
  4761.9 2330.77  4779.7 2322.13  4789.8 2320.09  4859.0 2316.26  4864.1 2317.21
  4950.5 2310.82  4960.5 2306.92  4966.2 2298.48  4971.2 2302.92  4980.6 2291.74
  5018.5 2291.15  5020.1 2288.74  5020.6 2288.24  5027.0 2288.74  5041.1 2293.84
  5098.7 2300.53  5173.7 2301.74  5212.4 2304.00  5259.0 2310.21  5333.4 2312.11
  5339.2 2314.47  5344.2 2314.32  5363.6 2321.23  5419.3 2334.91  5433.3 2336.63
#Mann=5,-1,0
  4673.2    0.16       0  4702.0    0.07       0  5020.1    0.07       0
  5027.0    0.07       0  5173.7    0.16       0
Bank Sta=5020.1,5027
Exp/Cntr=0.3,0.1

Type RM Length L Ch R = 1,23251,107,107,107
BEGIN DESCRIPTION:
Little Elm Creek 2 23251.32
END DESCRIPTION:
XS GIS Cut Line= 3
      1499315.88      6764668.89      1499659.67      6764668.89
      1500058.07      6764629.83
#Sta/Elev= 30
  4662.1 2337.49  4682.1 2335.70  4721.2 2332.34  4771.2 2326.68  4861.2 2319.56
  4901.2 2313.24  4931.2 2310.70  4941.2 2309.15  4951.2 2301.67  4971.2 2288.42
  4987.8 2286.62  4988.3 2286.12  4994.7 2286.62  5005.9 2286.64  5011.2 2289.11
  5021.3 2290.13  5041.4 2298.38  5051.4 2299.66  5122.5 2302.79  5172.9 2304.95
  5192.1 2308.51  5212.2 2310.05  5282.5 2310.21  5322.7 2311.31  5332.8 2312.89
  5370.8 2323.58  5375.9 2322.87  5383.0 2325.87  5402.2 2329.01  5406.2 2329.01
#Mann=5,-1,0
  4662.1    0.16       0  4682.1    0.07       0  4987.8    0.07       0
  4994.7    0.07       0  5122.5    0.16       0
Bank Sta=4987.8,4994.7
Exp/Cntr=0.3,0.1

Type RM Length L Ch R = 1,23144,171,171,171
BEGIN DESCRIPTION:
Little Elm Creek 2 23144.24
END DESCRIPTION:
XS GIS Cut Line= 3
      1499313.31      6764754.83      1499597.17      6764760.04
      1499904.42      6764765.25
#Sta/Elev= 30
  4708.0 2329.06  4780.5 2325.33  4789.7 2325.29  4809.7 2322.09  4829.7 2320.55
  4839.7 2319.17  4859.7 2318.44  4879.7 2315.91  4919.7 2312.32  4949.7 2311.23
  4979.7 2308.69  4988.3 2300.03  4991.9 2300.03  4999.7 2290.61  5009.7 2285.77
  5016.3 2284.79  5016.8 2284.29  5022.7 2284.29  5023.2 2284.79  5039.7 2288.94
  5049.7 2289.24  5059.7 2290.70  5069.8 2294.74  5089.8 2298.48  5146.0 2301.30
  5170.7 2303.06  5209.8 2304.60  5249.8 2307.37  5279.8 2307.42  5299.2 2308.60
#Mann=5,-1,0
  4708.0    0.16       0  4780.5    0.07       0  5016.3    0.07       0
  5023.2    0.07       0  5146.0    0.16       0
Bank Sta=5016.3,5023.2
Exp/Cntr=0.3,0.1

Type RM Length L Ch R = 1,22973,120,120,120
BEGIN DESCRIPTION:
Little Elm Creek 2 22973.47
END DESCRIPTION:
XS GIS Cut Line= 3
      1499162.26      6764869.41      1499610.19      6764885.04
      1499956.59      6764861.60
#Sta/Elev= 30
  4549.7 2322.47  4582.5 2322.32  4622.5 2320.95  4642.5 2319.94  4662.5 2317.51
  4722.5 2316.02  4762.6 2316.18  4780.2 2315.54  4832.6 2313.61  4862.6 2311.52
  4938.6 2308.10  4952.7 2305.36  4972.7 2294.92  4982.7 2290.64  4994.4 2289.56
  4994.9 2289.06  5000.8 2289.06  5001.3 2289.56  5022.8 2289.60  5041.2 2291.55
  5062.9 2295.60  5115.4 2297.69  5133.0 2300.96  5143.0 2301.70  5193.2 2304.58
  5283.4 2308.05  5324.5 2312.89  5333.5 2313.47  5341.8 2315.33  5345.1 2315.33
#Mann=7,-1,0
  4549.7    0.16       0  4780.2    0.07       0  4994.4    0.07       0
  5001.3    0.07       0  5041.2    0.16       0  5115.4    0.07       0
  5324.5    0.16       0
Bank Sta=4994.4,5001.3
Exp/Cntr=0.3,0.1

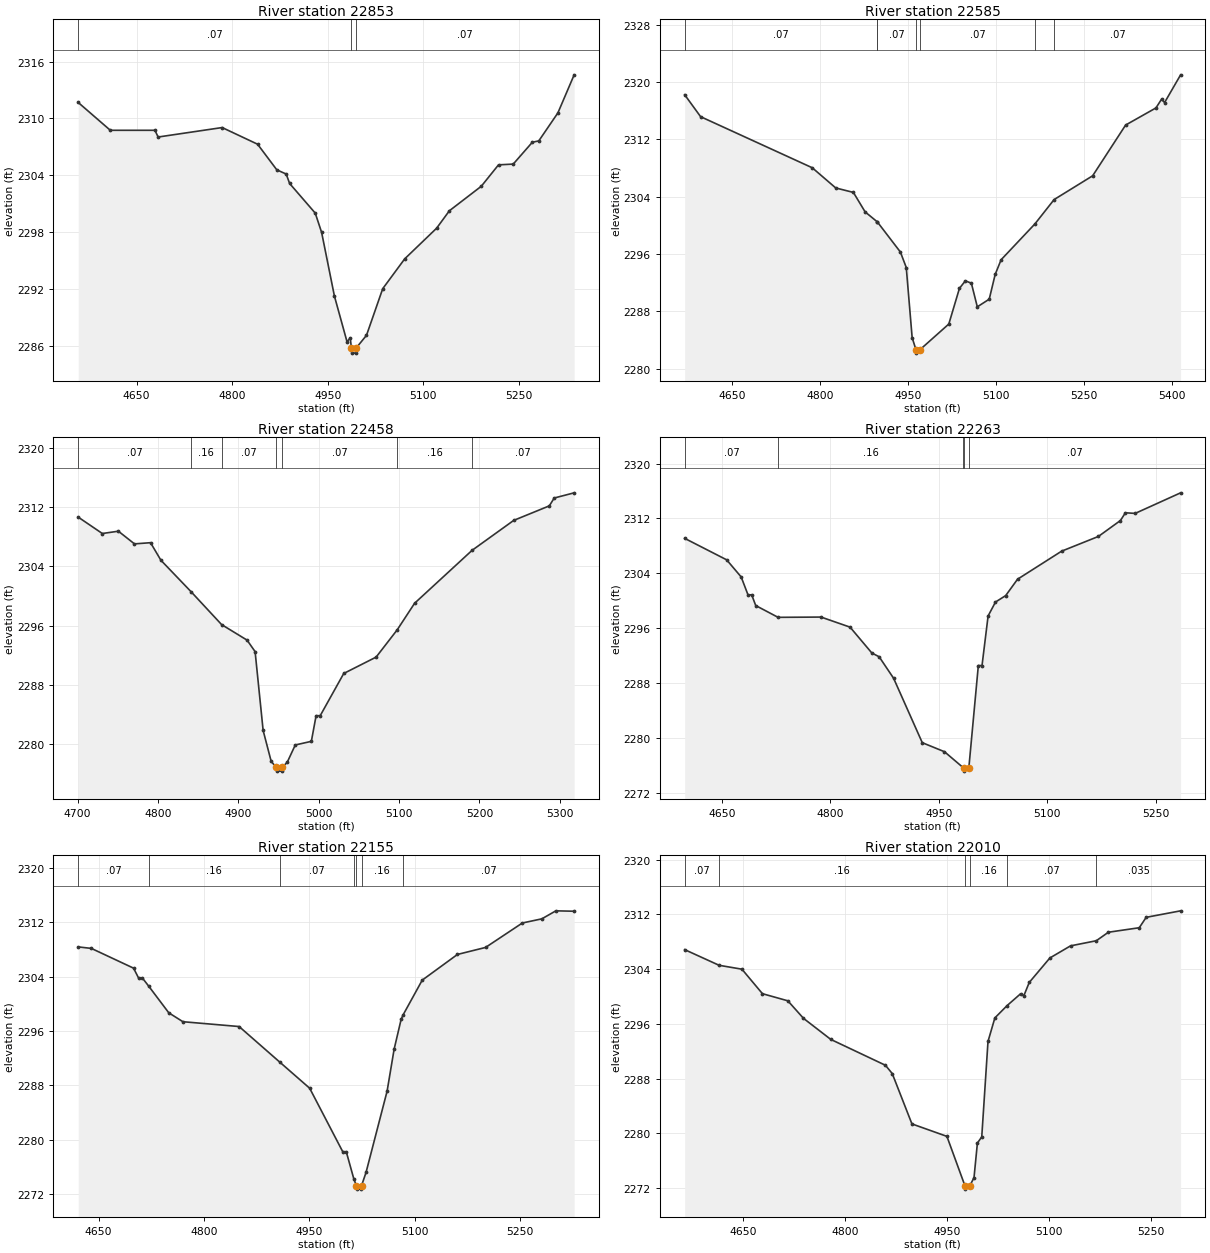
Type RM Length L Ch R = 1,22853,268,268,268
BEGIN DESCRIPTION:
Little Elm Creek 2 22852.54
END DESCRIPTION:
XS GIS Cut Line= 3
      1499164.87      6764960.56      1499607.59      6765004.83
      1499940.46      6764986.63
#Sta/Elev= 30
  4558.3 2311.68  4608.7 2308.74  4678.7 2308.74  4683.7 2308.03  4784.2 2309.03
  4839.8 2307.27  4870.0 2304.56  4884.7 2304.12  4890.1 2303.12  4930.3 2299.99
  4940.3 2297.95  4960.4 2291.22  4980.2 2286.39  4985.2 2286.82  4987.1 2285.70
  4987.6 2285.20  4993.5 2285.20  4994.0 2285.70  5010.7 2287.08  5036.2 2292.01
  5070.7 2295.16  5120.8 2298.40  5140.8 2300.24  5190.9 2302.83  5217.9 2305.09
  5241.0 2305.17  5271.0 2307.48  5281.1 2307.62  5311.1 2310.58  5336.6 2314.60
#Mann=3,-1,0
  4558.3    0.07       0  4987.1    0.07       0  4994.0    0.07       0
Bank Sta=4987.1,4994
Exp/Cntr=0.3,0.1

Type RM Length L Ch R = 1,22585,127,127,127
BEGIN DESCRIPTION:
Little Elm Creek 2 22584.52
END DESCRIPTION:
XS GIS Cut Line= 3
      1499177.94      6765228.79      1499604.98      6765226.18
      1500016.40      6765158.48
#Sta/Elev= 30
  4570.0 2318.21  4597.1 2315.15  4787.1 2308.02  4827.1 2305.20  4857.1 2304.58
  4877.1 2301.86  4897.5 2300.49  4898.0 2300.45  4937.1 2296.26  4947.1 2294.10
  4957.1 2284.32  4963.5 2282.65  4964.0 2282.15  4970.7 2282.65  5019.5 2286.21
  5037.6 2291.19  5047.7 2292.24  5057.9 2291.91  5068.0 2288.61  5088.3 2289.68
  5098.4 2293.13  5108.5 2295.18  5165.9 2300.17  5198.7 2303.58  5264.3 2306.90
  5320.4 2313.98  5372.0 2316.37  5381.6 2317.59  5386.7 2317.12  5414.0 2320.99
#Mann=7,-1,0
  4570.0    0.07       0  4897.5    0.16       0  4898.0    0.07       0
  4963.5    0.07       0  4970.7    0.07       0  5165.9    0.16       0
  5198.7    0.07       0
Bank Sta=4963.5,4970.7
Exp/Cntr=0.3,0.1

Type RM Length L Ch R = 1,22458,195,195,195
BEGIN DESCRIPTION:
Little Elm Creek 2 22457.61
END DESCRIPTION:
XS GIS Cut Line= 3
      1499355.00      6765330.35      1499651.86      6765338.16
      1499969.60      6765299.10
#Sta/Elev= 30
  4700.7 2310.66  4730.7 2308.45  4750.7 2308.76  4770.7 2307.05  4790.7 2307.21
  4803.6 2304.84  4841.0 2300.61  4879.1 2296.16  4910.8 2294.06  4920.8 2292.51
  4930.8 2281.87  4940.8 2277.70  4947.2 2276.88  4947.7 2276.38  4953.9 2276.38
  4954.4 2276.88  4960.8 2277.58  4970.8 2279.91  4990.8 2280.40  4996.7 2283.86
  5001.8 2283.86  5031.1 2289.56  5071.4 2291.77  5097.7 2295.46  5119.3 2299.04
  5190.8 2306.18  5242.6 2310.22  5286.9 2312.18  5293.0 2313.24  5317.8 2313.94
#Mann=7,-1,0
  4700.7    0.07       0  4841.0    0.16       0  4879.1    0.07       0
  4947.2    0.07       0  4954.4    0.07       0  5097.7    0.16       0
  5190.8    0.07       0
Bank Sta=4947.2,4954.4
Exp/Cntr=0.3,0.1

Type RM Length L Ch R = 1,22263,108,108,108
BEGIN DESCRIPTION:
Little Elm Creek 2 22263.07
END DESCRIPTION:
XS GIS Cut Line= 3
      1499347.18      6765455.35      1499753.42      6765489.20
      1500026.83      6765439.73
#Sta/Elev= 30
  4598.6 2309.10  4656.6 2305.97  4676.7 2303.47  4686.2 2300.84  4691.2 2300.87
  4696.8 2299.30  4727.7 2297.58  4787.1 2297.62  4827.2 2296.15  4857.3 2292.38
  4867.4 2291.83  4887.4 2288.69  4927.0 2279.30  4957.7 2277.98  4983.0 2275.71
  4984.1 2275.65  4984.6 2275.15  4991.4 2275.65  5004.5 2290.55  5009.6 2290.55
  5018.0 2297.78  5028.2 2299.81  5042.3 2300.75  5058.7 2303.14  5119.6 2307.23
  5170.5 2309.38  5200.9 2311.70  5207.8 2312.83  5221.3 2312.74  5284.1 2315.74
#Mann=5,-1,0
  4598.6    0.07       0  4727.7    0.16       0  4983.0    0.07       0
  4984.1    0.07       0  4991.4    0.07       0
Bank Sta=4984.1,4991.4
Exp/Cntr=0.3,0.1

Type RM Length L Ch R = 1,22155,145,145,145
BEGIN DESCRIPTION:
Little Elm Creek 2 22155.24
END DESCRIPTION:
XS GIS Cut Line= 3
      1499326.37      6765556.91      1499703.94      6765582.95
      1500031.01      6765569.98
#Sta/Elev= 30
  4620.9 2308.39  4639.6 2308.17  4699.7 2305.26  4707.0 2303.77  4712.1 2303.83
  4721.1 2302.63  4749.8 2298.69  4769.9 2297.38  4849.9 2296.67  4907.9 2291.42
  4950.3 2287.59  4997.4 2278.24  5002.4 2278.24  5013.1 2274.26  5016.8 2273.24
  5017.3 2272.74  5023.6 2272.74  5024.1 2273.24  5030.5 2275.19  5060.5 2287.16
  5070.5 2293.34  5080.5 2297.74  5083.4 2298.41  5110.5 2303.50  5160.6 2307.28
  5200.6 2308.31  5253.0 2311.91  5280.7 2312.52  5300.7 2313.70  5326.7 2313.64
#Mann=7,-1,0
  4620.9    0.07       0  4721.1    0.16       0  4907.9    0.07       0
  5013.1    0.16       0  5016.8    0.07       0  5024.1    0.16       0
  5083.4    0.07       0
Bank Sta=5016.8,5024.1
Exp/Cntr=0.3,0.1

Type RM Length L Ch R = 1,22010,207,207,207
BEGIN DESCRIPTION:
Little Elm Creek 2 22009.79
END DESCRIPTION:
XS GIS Cut Line= 3
      1499321.17      6765666.29      1499750.82      6765713.16
      1500045.11      6765666.28
#Sta/Elev= 30
  4563.9 2306.85  4614.6 2304.56  4648.2 2303.99  4678.4 2300.41  4715.8 2299.37
  4738.8 2296.81  4779.0 2293.73  4859.5 2289.95  4869.5 2288.74  4898.5 2281.38
  4950.0 2279.56  4976.5 2272.35  4977.0 2271.85  4983.8 2272.35  4989.9 2273.53
  4994.9 2278.59  5001.3 2279.48  5010.5 2293.43  5020.6 2296.87  5038.7 2298.68
  5058.4 2300.39  5063.4 2300.14  5071.2 2302.05  5101.6 2305.63  5132.0 2307.40
  5170.0 2308.15  5187.7 2309.39  5233.2 2310.05  5243.4 2311.57  5294.1 2312.52
#Mann=6,-1,0
  4563.9    0.07       0  4614.6    0.16       0  4976.5    0.07       0
  4983.8    0.16       0  5038.7    0.07       0  5170.0   0.035       0
Bank Sta=4976.5,4983.8
Exp/Cntr=0.3,0.1

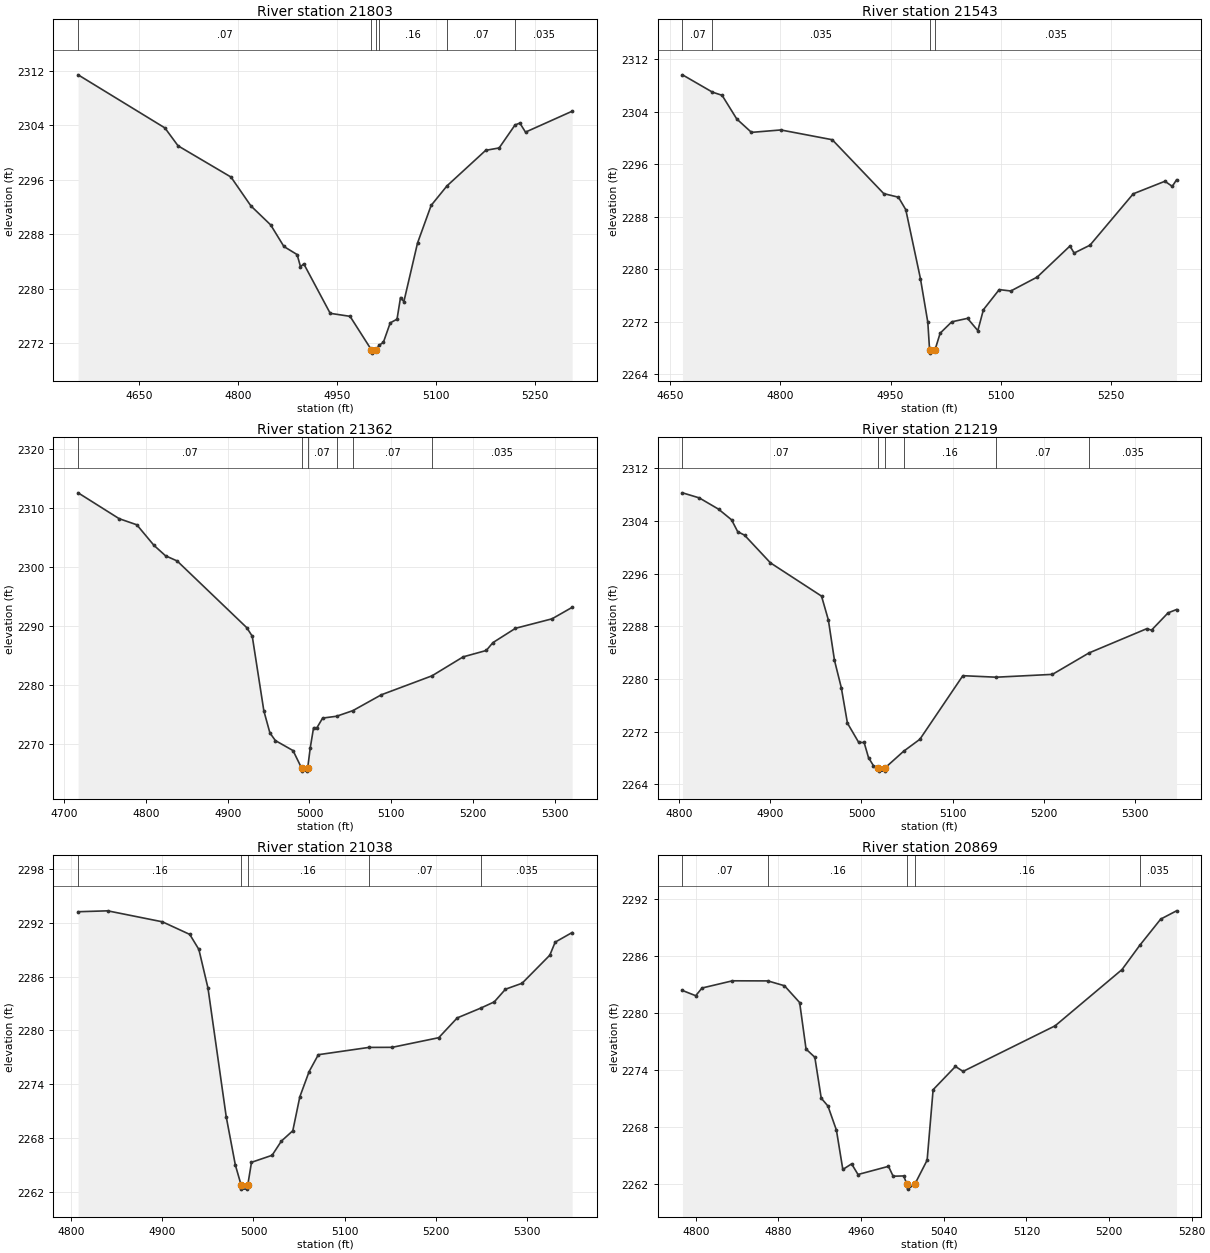
Type RM Length L Ch R = 1,21803,260,260,260
BEGIN DESCRIPTION:
Little Elm Creek 2 21802.75
END DESCRIPTION:
XS GIS Cut Line= 3
      1499263.84      6765942.33      1499711.76      6765903.27
      1500001.72      6765825.60
#Sta/Elev= 30
  4557.3 2311.39  4689.0 2303.60  4709.0 2300.97  4789.3 2296.39  4819.5 2292.16
  4849.6 2289.36  4869.6 2286.20  4889.7 2285.01  4894.8 2283.23  4899.8 2283.65
  4939.9 2276.39  4970.0 2275.95  5002.3 2271.05  5002.8 2270.55  5009.7 2271.05
  5014.0 2271.69  5020.6 2272.14  5031.0 2274.99  5041.3 2275.53  5046.6 2278.71
  5051.7 2278.11  5072.4 2286.70  5093.1 2292.23  5117.2 2295.10  5175.9 2300.31
  5196.3 2300.66  5220.4 2304.03  5227.7 2304.31  5236.3 2302.98  5307.1 2306.05
#Mann=6,-1,0
  4557.3    0.07       0  5002.3    0.07       0  5009.7    0.07       0
  5014.0    0.16       0  5117.2    0.07       0  5220.4   0.035       0
Bank Sta=5002.3,5009.7
Exp/Cntr=0.3,0.1

Type RM Length L Ch R = 1,21543,181,181,181
BEGIN DESCRIPTION:
Little Elm Creek 2 21543.28
END DESCRIPTION:
XS GIS Cut Line= 3
      1499321.17      6766137.64      1499662.28      6766148.06
      1499949.32      6765982.56
#Sta/Elev= 30
  4666.7 2309.60  4707.5 2306.96  4720.6 2306.48  4740.6 2302.87  4760.6 2300.83
  4800.6 2301.20  4870.6 2299.71  4940.7 2291.50  4960.7 2290.95  4970.7 2289.05
  4990.7 2278.52  5000.7 2271.89  5003.1 2267.69  5003.6 2267.19  5010.5 2267.69
  5017.5 2270.23  5033.3 2271.96  5054.8 2272.49  5068.8 2270.62  5076.4 2273.81
  5097.9 2276.87  5113.7 2276.66  5149.6 2278.78  5194.2 2283.51  5199.9 2282.44
  5221.5 2283.64  5280.4 2291.47  5323.5 2293.38  5333.5 2292.60  5339.3 2293.60
#Mann=4,-1,0
  4666.7    0.07       0  4707.5   0.035       0  5003.1   0.035       0
  5010.5   0.035       0
Bank Sta=5003.1,5010.5
Exp/Cntr=0.3,0.1

Type RM Length L Ch R = 1,21362,143,143,143
BEGIN DESCRIPTION:
Little Elm Creek 2 21361.55
END DESCRIPTION:
XS GIS Cut Line= 3
      1499568.51      6766452.76      1499782.07      6766257.43
      1499960.90      6765998.26
#Sta/Elev= 30
  4717.0 2312.61  4767.2 2308.22  4788.8 2307.18  4809.7 2303.70  4823.9 2301.92
  4838.1 2301.04  4923.2 2289.72  4930.0 2288.26  4944.2 2275.57  4951.6 2271.83
  4958.3 2270.53  4979.9 2268.83  4990.4 2265.84  4990.9 2265.34  4997.3 2265.34
  4997.8 2265.84  5000.9 2269.26  5005.0 2272.71  5009.1 2272.71  5016.1 2274.35
  5033.1 2274.66  5053.0 2275.61  5087.8 2278.30  5149.9 2281.53  5188.0 2284.75
  5216.2 2285.83  5224.4 2287.17  5252.0 2289.60  5296.7 2291.21  5321.3 2293.16
#Mann=6,-1,0
  4717.0    0.07       0  4990.4    0.07       0  4997.8    0.07       0
  5033.1    0.16       0  5053.0    0.07       0  5149.9   0.035       0
Bank Sta=4990.4,4997.8
Exp/Cntr=0.3,0.1

Type RM Length L Ch R = 1,21219,181,181,181
BEGIN DESCRIPTION:
Little Elm Creek 2 21219.46
END DESCRIPTION:
XS GIS Cut Line= 3
      1499701.31      6766510.06      1499847.17      6766379.83
      1499948.73      6766049.11
#Sta/Elev= 30
  4803.8 2308.28  4822.2 2307.51  4843.3 2305.80  4857.6 2304.18  4864.3 2302.38
  4871.8 2301.85  4900.2 2297.64  4956.2 2292.59  4963.7 2288.96  4970.4 2282.83
  4977.9 2278.66  4984.6 2273.29  4997.0 2270.35  5002.9 2270.35  5007.7 2268.05
  5013.0 2266.85  5018.4 2266.50  5018.9 2266.00  5025.4 2266.00  5025.9 2266.50
  5046.1 2269.01  5064.0 2270.84  5111.1 2280.50  5147.7 2280.27  5209.3 2280.70
  5249.3 2283.95  5312.7 2287.64  5317.9 2287.42  5336.0 2290.04  5345.3 2290.55
#Mann=6,-1,0
  4803.8    0.07       0  5018.4    0.07       0  5025.9    0.07       0
  5046.1    0.16       0  5147.7    0.07       0  5249.3   0.035       0
Bank Sta=5018.4,5025.9
Exp/Cntr=0.3,0.1

Type RM Length L Ch R = 1,21038,169,169,169
BEGIN DESCRIPTION:
Little Elm Creek 2 21038.1
END DESCRIPTION:
XS GIS Cut Line= 3
      1500024.25      6766580.37      1500026.86      6766387.64
      1499966.96      6766043.87
#Sta/Elev= 30
  4807.7 2293.20  4840.1 2293.30  4900.1 2292.08  4930.1 2290.68  4940.1 2289.01
  4950.1 2284.71  4970.1 2270.41  4980.1 2265.05  4986.3 2262.87  4986.8 2262.37
  4993.3 2262.37  4993.8 2262.87  4997.8 2265.35  5020.4 2266.13  5030.5 2267.70
  5043.1 2268.86  5050.8 2272.63  5061.0 2275.44  5071.1 2277.31  5126.5 2278.12
  5152.1 2278.13  5203.1 2279.20  5223.4 2281.40  5249.2 2282.49  5264.0 2283.18
  5276.3 2284.59  5294.5 2285.25  5324.9 2288.37  5330.8 2289.82  5349.4 2290.89
#Mann=5,-1,0
  4807.7    0.16       0  4986.3    0.07       0  4993.8    0.16       0
  5126.5    0.07       0  5249.2   0.035       0
Bank Sta=4986.3,4993.8
Exp/Cntr=0.3,0.1

Type RM Length L Ch R = 1,20869,123,123,123
BEGIN DESCRIPTION:
Little Elm Creek 2 20869.36
END DESCRIPTION:
XS GIS Cut Line= 3
      1500248.20      6766442.31      1500128.42      6766275.66
      1499992.99      6766038.65
#Sta/Elev= 30
  4787.1 2282.38  4799.9 2281.83  4806.0 2282.64  4835.5 2283.40  4869.7 2283.39
  4885.8 2282.88  4900.5 2281.11  4906.7 2276.21  4915.2 2275.35  4921.4 2271.04
  4927.9 2270.21  4936.1 2267.67  4942.3 2263.53  4950.8 2264.12  4957.0 2263.00
  4986.5 2263.86  4991.0 2262.82  5001.2 2262.85  5004.4 2261.96  5004.9 2261.46
  5011.9 2261.96  5023.9 2264.51  5029.7 2271.93  5051.3 2274.38  5058.7 2273.86
  5147.8 2278.66  5212.5 2284.58  5229.6 2287.12  5250.0 2289.90  5265.3 2290.77
#Mann=5,-1,0
  4787.1    0.07       0  4869.7    0.16       0  5004.4    0.07       0
  5011.9    0.16       0  5229.6   0.035       0
Bank Sta=5004.4,5011.9
Exp/Cntr=0.3,0.1