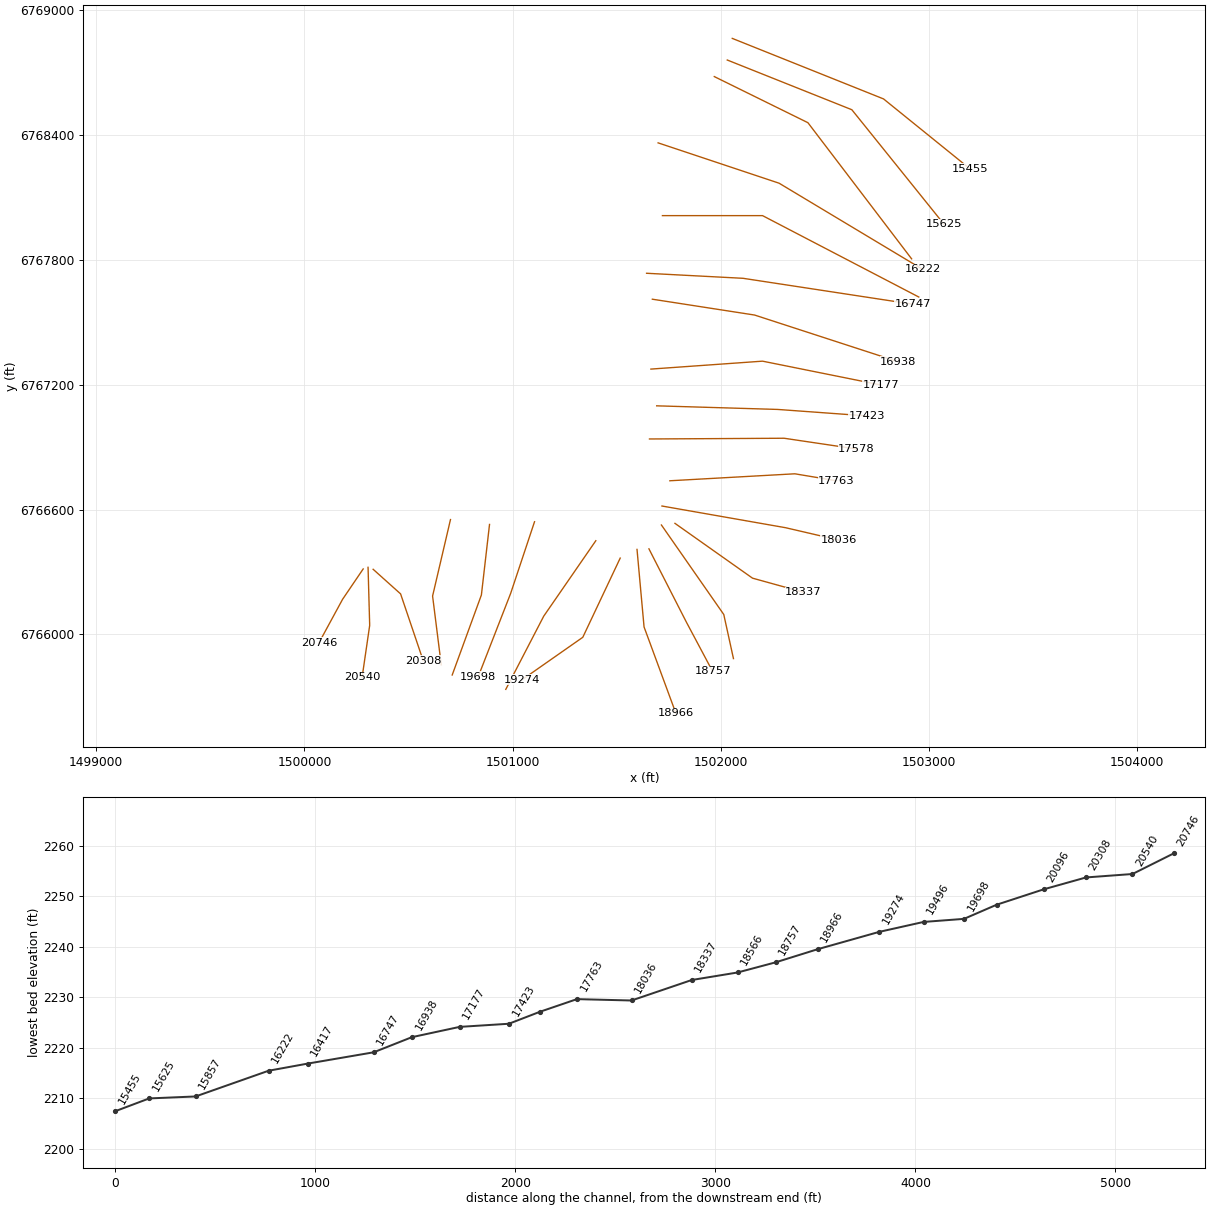
HEC-RAS study Little Elm Creek 2.prj: Little Elm Creek 2 Base Level Engineering

--- Little Elm Creek 2.g01 (geometry) --- (continued)

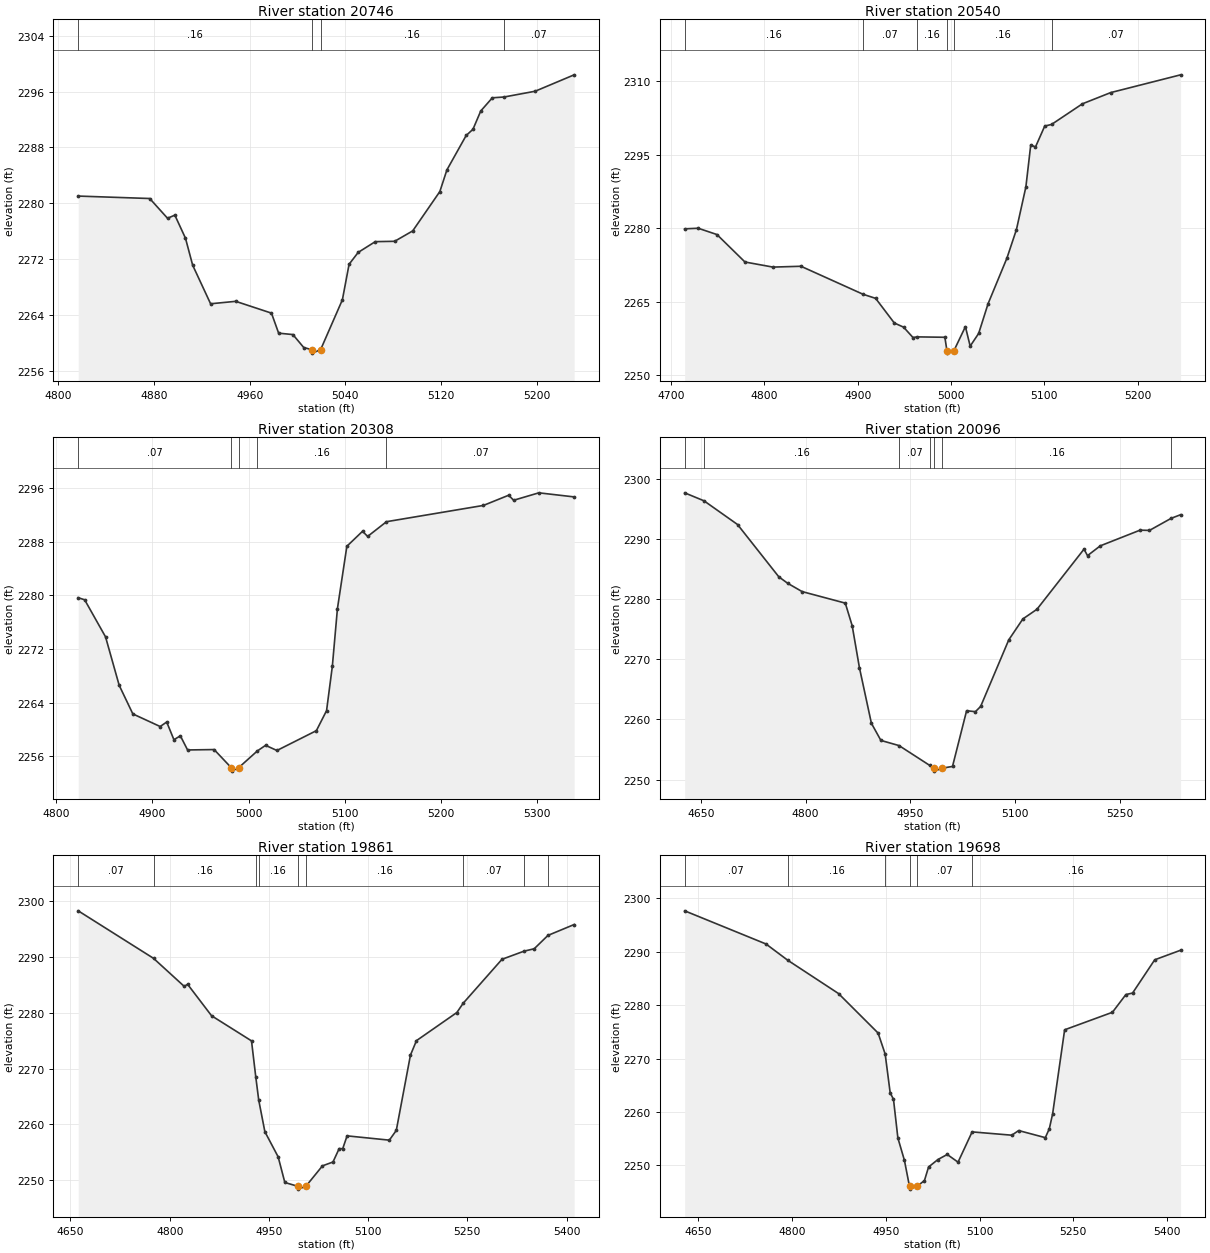
Type RM Length L Ch R = 1,20746,206,206,206
BEGIN DESCRIPTION:
Little Elm Creek 2 20746.17
END DESCRIPTION:
XS GIS Cut Line= 3
      1500282.06      6766314.71      1500183.11      6766168.89
      1500069.28      6765959.34
#Sta/Elev= 30
  4816.6 2281.03  4876.4 2280.68  4891.3 2277.85  4897.4 2278.30  4906.3 2274.99
  4912.3 2271.13  4927.3 2265.60  4948.3 2265.95  4978.2 2264.26  4984.2 2261.39
  4996.1 2261.19  5005.2 2259.33  5011.8 2259.03  5012.3 2258.53  5019.3 2259.03
  5037.5 2266.17  5043.1 2271.26  5050.7 2272.96  5065.0 2274.50  5081.2 2274.55
  5096.3 2276.04  5119.0 2281.68  5124.9 2284.78  5141.0 2289.71  5146.7 2290.60
  5153.2 2293.22  5162.9 2295.11  5172.6 2295.22  5198.7 2296.05  5231.3 2298.40
#Mann=4,-1,0
  4816.6    0.16       0  5011.8    0.07       0  5019.3    0.16       0
  5172.6    0.07       0
Bank Sta=5011.8,5019.3
Exp/Cntr=0.3,0.1

Type RM Length L Ch R = 1,20540,232,232,232
BEGIN DESCRIPTION:
Little Elm Creek 2 20540.38
END DESCRIPTION:
XS GIS Cut Line= 3
      1500305.50      6766322.54      1500313.32      6766043.89
      1500276.86      6765793.90
#Sta/Elev= 30
  4714.6 2279.85  4729.1 2279.97  4749.2 2278.68  4779.2 2273.07  4809.2 2272.03
  4839.2 2272.20  4905.7 2266.48  4919.2 2265.64  4939.2 2260.61  4949.2 2259.75
  4959.2 2257.64  4963.6 2257.77  4993.4 2257.69  4995.6 2254.95  4996.1 2254.45
  5003.1 2254.95  5015.4 2259.86  5020.5 2255.88  5029.6 2258.47  5039.7 2264.55
  5059.9 2273.87  5070.1 2279.71  5080.2 2288.42  5085.4 2296.98  5090.5 2296.58
  5100.4 2300.85  5107.7 2301.18  5140.8 2305.40  5171.1 2307.69  5246.0 2311.32
#Mann=6,-1,0
  4714.6    0.16       0  4905.7    0.07       0  4963.6    0.16       0
  4995.6    0.07       0  5003.1    0.16       0  5107.7    0.07       0
Bank Sta=4995.6,5003.1
Exp/Cntr=0.3,0.1

Type RM Length L Ch R = 1,20308,212,212,212
BEGIN DESCRIPTION:
Little Elm Creek 2 20308.3
END DESCRIPTION:
XS GIS Cut Line= 3
      1500329.99      6766313.01      1500461.76      6766194.93
      1500570.40      6765874.16
#Sta/Elev= 30
  4822.9 2279.66  4829.6 2279.35  4851.3 2273.82  4865.5 2266.58  4879.7 2262.31
  4908.1 2260.43  4914.9 2261.10  4922.4 2258.46  4929.1 2259.04  4936.6 2256.93
  4964.2 2256.99  4982.1 2254.27  4982.6 2253.77  4989.6 2254.27  5009.1 2256.78
  5017.7 2257.62  5029.5 2256.85  5070.5 2259.81  5081.1 2262.80  5087.1 2269.42
  5092.4 2278.04  5102.2 2287.34  5118.5 2289.58  5123.8 2288.81  5143.4 2291.01
  5244.2 2293.44  5270.4 2294.96  5275.6 2294.21  5301.8 2295.32  5338.5 2294.71
#Mann=5,-1,0
  4822.9    0.07       0  4982.1    0.07       0  4989.6    0.07       0
  5009.1    0.16       0  5143.4    0.07       0
Bank Sta=4982.1,4989.6
Exp/Cntr=0.3,0.1

Type RM Length L Ch R = 1,20096,235,235,235
BEGIN DESCRIPTION:
Little Elm Creek 2 20095.64
END DESCRIPTION:
XS GIS Cut Line= 3
      1500701.34      6766551.73      1500615.40      6766184.52
      1500657.07      6765853.77
#Sta/Elev= 30
  4626.8 2297.71  4654.5 2296.38  4702.5 2292.44  4761.7 2283.73  4774.4 2282.66
  4795.0 2281.28  4856.9 2279.36  4866.8 2275.59  4877.1 2268.65  4894.3 2259.37
  4907.9 2256.52  4933.9 2255.66  4977.9 2252.36  4984.2 2251.91  4984.7 2251.41
  4996.0 2251.91  5010.5 2252.19  5030.7 2261.46  5043.3 2261.30  5050.8 2262.17
  5091.1 2273.25  5111.3 2276.73  5131.5 2278.34  5198.9 2288.34  5203.9 2287.26
  5222.2 2288.89  5279.2 2291.50  5292.7 2291.46  5323.8 2293.47  5337.3 2294.07
#Mann=7,-1,0
  4626.8    0.07       0  4654.5    0.16       0  4933.9    0.07       0
  4977.9    0.16       0  4984.2    0.07       0  4996.0    0.16       0
  5323.8    0.07       0
Bank Sta=4984.2,4996
Exp/Cntr=0.3,0.1

Type RM Length L Ch R = 1,19861,163,163,163
BEGIN DESCRIPTION:
Little Elm Creek 2 19861.25
END DESCRIPTION:
XS GIS Cut Line= 3
      1500888.84      6766528.29      1500849.78      6766189.73
      1500709.59      6765805.51
#Sta/Elev= 30
  4661.7 2298.31  4775.6 2289.78  4822.0 2284.75  4827.1 2285.12  4863.3 2279.48
  4923.7 2274.97  4930.1 2268.55  4934.6 2264.35  4943.9 2258.67  4964.0 2254.15
  4974.1 2249.55  4994.0 2248.86  4994.5 2248.36  5005.8 2248.86  5031.0 2252.54
  5046.9 2253.23  5056.2 2255.63  5061.6 2255.62  5068.2 2257.92  5132.1 2257.15
  5142.6 2258.90  5164.0 2272.41  5173.1 2275.01  5234.2 2280.06  5243.7 2281.72
  5302.4 2289.61  5335.7 2291.07  5351.1 2291.50  5371.9 2293.90  5411.5 2295.85
#Mann=9,-1,0
  4661.7    0.07       0  4775.6    0.16       0  4930.1    0.07       0
  4934.6    0.16       0  4994.0    0.07       0  5005.8    0.16       0
  5243.7    0.07       0  5335.7    0.16       0  5371.9    0.07       0
Bank Sta=4994,5005.8
Exp/Cntr=0.3,0.1

Type RM Length L Ch R = 1,19698,202,202,202
BEGIN DESCRIPTION:
Little Elm Creek 2 19697.81
END DESCRIPTION:
XS GIS Cut Line= 3
      1501104.99      6766541.31      1500990.40      6766197.54
      1500834.14      6765796.48
#Sta/Elev= 30
  4628.7 2297.68  4758.7 2291.47  4793.4 2288.43  4874.6 2282.19  4937.9 2274.79
  4949.2 2270.86  4957.2 2263.60  4962.5 2262.38  4969.5 2255.15  4980.0 2250.94
  4988.1 2246.06  4988.6 2245.56  5000.0 2246.06  5012.0 2247.17  5018.6 2249.71
  5033.5 2251.10  5048.4 2252.05  5065.7 2250.61  5088.2 2256.28  5151.6 2255.66
  5162.6 2256.53  5205.2 2255.20  5211.6 2256.87  5216.9 2259.66  5236.1 2275.40
  5312.5 2278.68  5334.0 2282.00  5344.7 2282.28  5380.1 2288.51  5421.5 2290.30
#Mann=6,-1,0
  4628.7    0.07       0  4793.4    0.16       0  4949.2    0.07       0
  4988.1    0.07       0  5000.0    0.07       0  5088.2    0.16       0
Bank Sta=4988.1,5000
Exp/Cntr=0.3,0.1

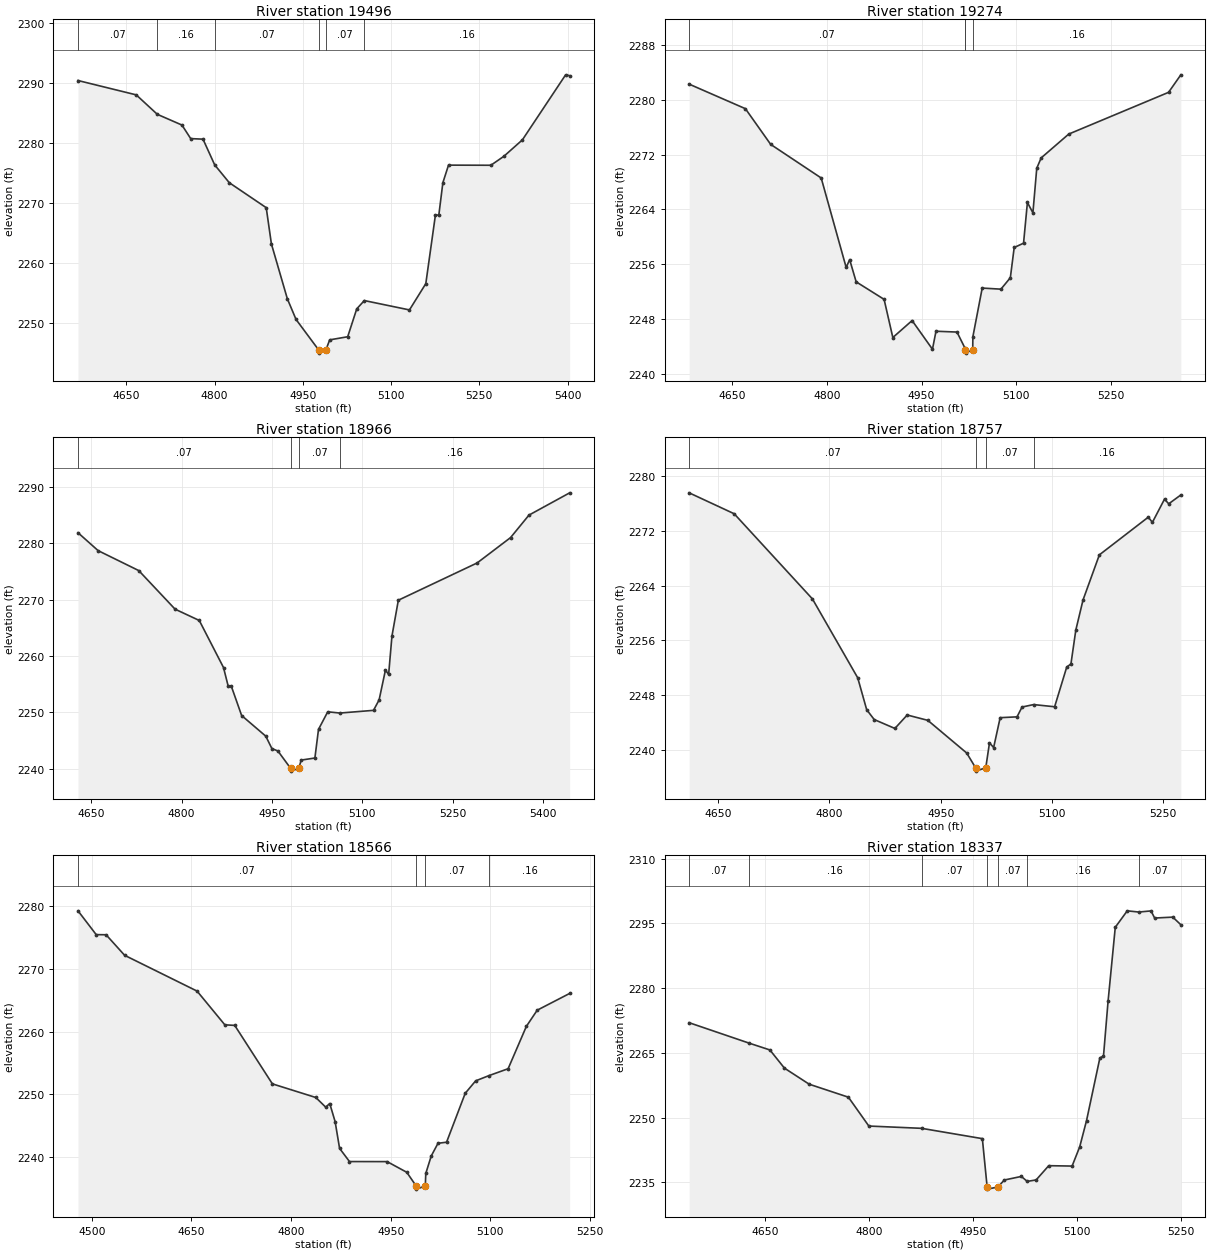
Type RM Length L Ch R = 1,19496,222,222,222
BEGIN DESCRIPTION:
Little Elm Creek 2 19496.19
END DESCRIPTION:
XS GIS Cut Line= 3
      1501399.24      6766450.13      1501149.26      6766088.16
      1500966.97      6765736.61
#Sta/Elev= 30
  4567.7 2290.38  4666.7 2287.99  4702.5 2284.75  4744.4 2282.96  4759.3 2280.70
  4780.2 2280.61  4800.1 2276.32  4824.9 2273.35  4887.7 2269.19  4896.5 2263.15
  4923.6 2254.01  4938.4 2250.56  4977.1 2245.45  4977.6 2244.95  4989.0 2245.45
  4995.6 2247.16  5026.2 2247.68  5041.6 2252.33  5054.5 2253.71  5131.2 2252.15
  5159.0 2256.53  5175.4 2268.00  5181.1 2267.93  5188.0 2273.35  5197.6 2276.28
  5269.6 2276.26  5291.7 2277.75  5323.2 2280.49  5396.7 2291.33  5403.6 2291.18
#Mann=6,-1,0
  4567.7    0.07       0  4702.5    0.16       0  4800.1    0.07       0
  4977.1    0.07       0  4989.0    0.07       0  5054.5    0.16       0
Bank Sta=4977.1,4989
Exp/Cntr=0.3,0.1

Type RM Length L Ch R = 1,19274,308,308,308
BEGIN DESCRIPTION:
Little Elm Creek 2 19274.41
END DESCRIPTION:
XS GIS Cut Line= 3
      1501516.46      6766366.84      1501336.76      6765986.60
      1501043.98      6765781.92
#Sta/Elev= 30
  4582.3 2282.30  4671.3 2278.71  4711.3 2273.49  4791.2 2268.58  4830.7 2255.50
  4836.2 2256.65  4846.5 2253.40  4890.7 2250.84  4904.5 2245.26  4935.0 2247.74
  4967.2 2243.55  4972.8 2246.18  5006.0 2246.06  5018.4 2243.75  5019.0 2243.48
  5019.5 2242.98  5030.9 2243.48  5031.1 2245.36  5045.9 2252.49  5075.5 2252.33
  5090.4 2254.00  5096.5 2258.42  5111.3 2259.05  5117.4 2265.00  5126.1 2263.49
  5132.2 2270.01  5139.2 2271.52  5182.8 2275.00  5340.7 2281.10  5360.1 2283.66
#Mann=4,-1,0
  4582.3    0.07       0  5018.4    0.16       0  5019.0    0.07       0
  5030.9    0.16       0
Bank Sta=5019,5030.9
Exp/Cntr=0.3,0.1

Type RM Length L Ch R = 1,18966,209,209,209
BEGIN DESCRIPTION:
Little Elm Creek 2 18965.74
END DESCRIPTION:
XS GIS Cut Line= 3
      1501597.17      6766408.47      1501631.03      6766036.08
      1501784.01      6765621.21
#Sta/Elev= 30
  4628.1 2281.90  4661.5 2278.72  4729.0 2275.17  4789.2 2268.32  4829.4 2266.31
  4869.6 2257.95  4877.4 2254.63  4882.4 2254.68  4899.7 2249.42  4939.8 2245.75
  4949.9 2243.55  4959.9 2243.12  4981.0 2240.04  4981.5 2239.54  4994.7 2240.04
  4998.5 2241.50  5021.3 2241.87  5027.3 2246.96  5042.6 2250.08  5062.8 2249.86
  5118.6 2250.34  5127.9 2252.20  5138.4 2257.50  5143.7 2256.72  5149.2 2263.54
  5159.8 2269.91  5290.6 2276.53  5346.1 2281.04  5376.6 2285.03  5444.2 2288.99
#Mann=4,-1,0
  4628.1    0.07       0  4981.0    0.07       0  4994.7    0.07       0
  5062.8    0.16       0
Bank Sta=4981,4994.7
Exp/Cntr=0.3,0.1

Type RM Length L Ch R = 1,18757,191,191,191
BEGIN DESCRIPTION:
Little Elm Creek 2 18756.58
END DESCRIPTION:
XS GIS Cut Line= 3
      1501654.45      6766411.11      1501834.15      6766059.52
      1501960.06      6765823.12
#Sta/Elev= 30
  4610.9 2277.51  4671.6 2274.46  4777.1 2262.04  4838.1 2250.55  4850.2 2245.90
  4860.3 2244.47  4888.2 2243.17  4904.8 2245.13  4932.6 2244.35  4985.0 2239.59
  4996.9 2237.45  4997.4 2236.95  5010.7 2237.45  5015.7 2241.07  5021.3 2240.39
  5030.1 2244.74  5052.8 2244.86  5059.6 2246.29  5075.2 2246.65  5103.5 2246.33
  5119.8 2252.11  5125.5 2252.58  5132.1 2257.53  5141.8 2261.90  5163.8 2268.47
  5229.7 2273.96  5235.3 2273.21  5251.6 2276.59  5257.3 2275.91  5273.6 2277.20
#Mann=4,-1,0
  4610.9    0.07       0  4996.9    0.07       0  5010.7    0.07       0
  5075.2    0.16       0
Bank Sta=4996.9,5010.7
Exp/Cntr=0.3,0.1

Type RM Length L Ch R = 1,18566,229,229,229
BEGIN DESCRIPTION:
Little Elm Creek 2 18566.41
END DESCRIPTION:
XS GIS Cut Line= 3
      1501714.38      6766525.63      1502013.84      6766095.98
      1502060.30      6765884.33
#Sta/Elev= 30
  4479.1 2279.24  4506.5 2275.45  4521.4 2275.43  4549.3 2272.16  4658.4 2266.46
  4700.2 2261.09  4715.1 2261.00  4771.8 2251.69  4837.2 2249.52  4852.1 2247.98
  4858.2 2248.56  4866.3 2245.67  4873.0 2241.42  4887.9 2239.32  4944.6 2239.31
  4974.2 2237.61  4988.3 2235.43  4988.8 2234.93  5002.1 2235.43  5002.8 2237.42
  5011.0 2240.20  5021.2 2242.23  5034.1 2242.40  5062.2 2250.19  5077.9 2252.17
  5098.1 2253.01  5126.8 2254.10  5154.3 2260.85  5170.6 2263.42  5219.5 2266.09
#Mann=4,-1,0
  4479.1    0.07       0  4988.3    0.07       0  5002.1    0.07       0
  5098.1    0.16       0
Bank Sta=4988.3,5002.1
Exp/Cntr=0.3,0.1

Type RM Length L Ch R = 1,18337,301,301,301
BEGIN DESCRIPTION:
Little Elm Creek 2 18337.47
END DESCRIPTION:
XS GIS Cut Line= 3
      1501779.42      6766533.50      1502151.86      6766270.45
      1502396.22      6766202.87
#Sta/Elev= 30
  4540.6 2271.98  4626.4 2267.29  4657.1 2265.67  4678.1 2261.46  4713.8 2257.74
  4770.4 2254.73  4799.9 2248.05  4876.0 2247.52  4963.7 2245.13  4970.6 2233.94
  4971.1 2233.44  4986.2 2233.94  4995.4 2235.55  5020.0 2236.38  5028.4 2235.23
  5041.3 2235.57  5059.5 2238.87  5093.2 2238.78  5104.2 2243.24  5114.0 2249.29
  5133.3 2263.83  5138.5 2264.24  5145.1 2276.94  5155.5 2294.08  5172.8 2297.89
  5189.4 2297.61  5207.1 2297.87  5212.3 2296.22  5238.5 2296.43  5250.1 2294.67
#Mann=7,-1,0
  4540.6    0.07       0  4626.4    0.16       0  4876.0    0.07       0
  4970.6    0.07       0  4986.2    0.07       0  5028.4    0.16       0
  5189.4    0.07       0
Bank Sta=4970.6,4986.2
Exp/Cntr=0.3,0.1

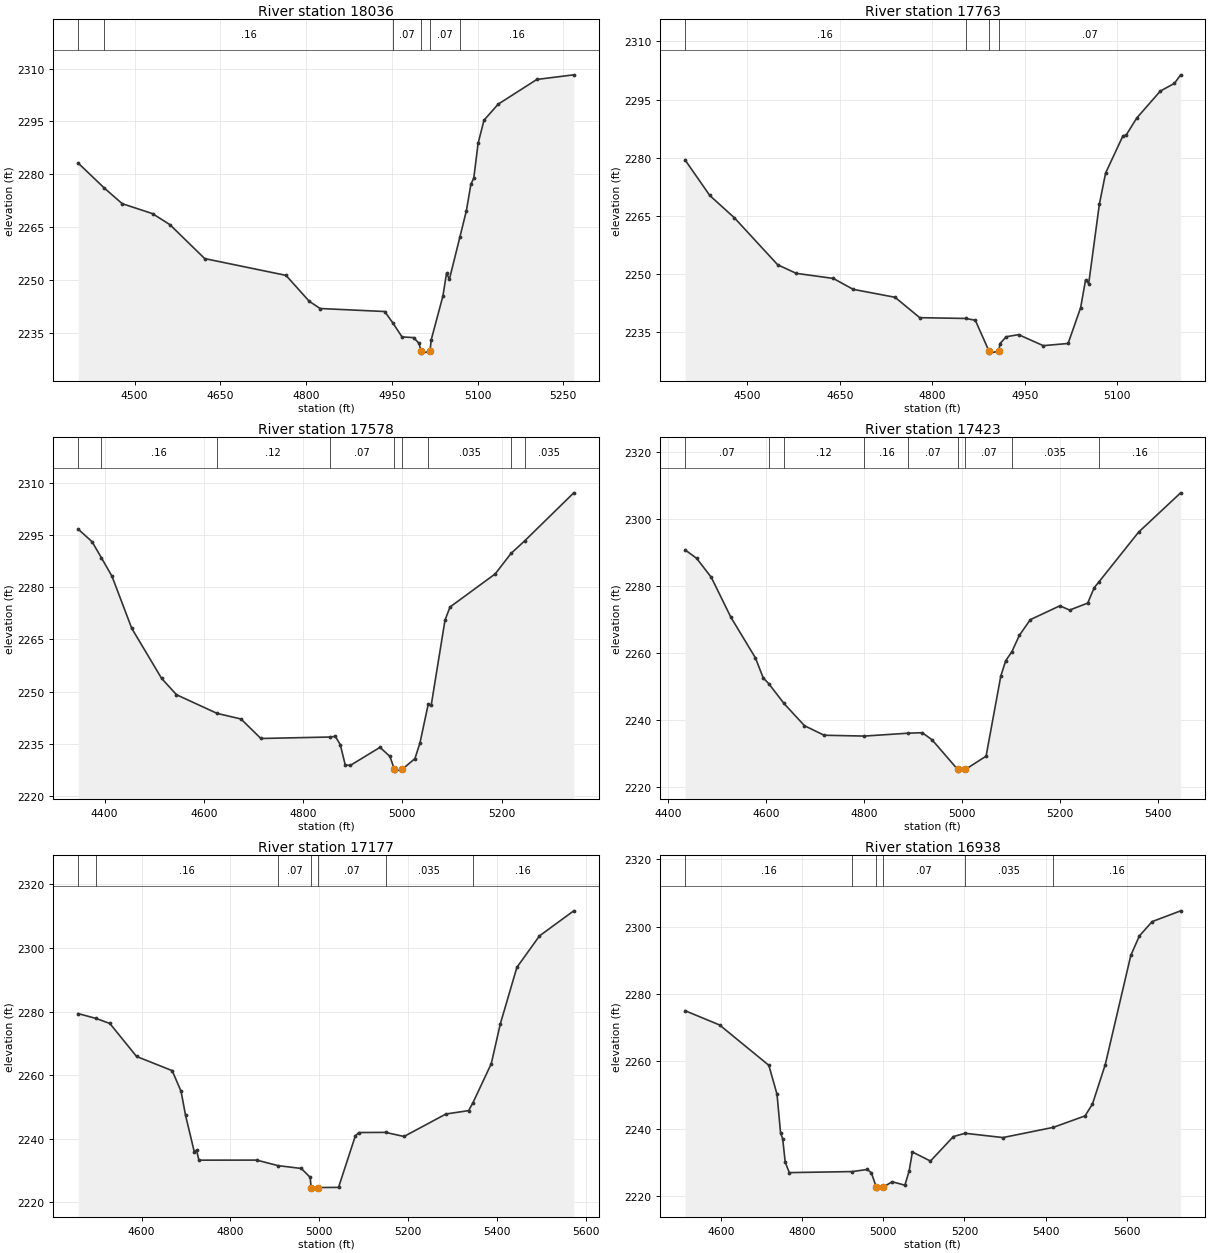
Type RM Length L Ch R = 1,18036,273,273,273
BEGIN DESCRIPTION:
Little Elm Creek 2 18036.31
END DESCRIPTION:
XS GIS Cut Line= 3
      1501716.98      6766616.81      1502310.71      6766512.64
      1502567.96      6766452.88
#Sta/Elev= 30
  4401.3 2283.22  4447.3 2276.10  4478.3 2271.72  4531.3 2268.90  4561.7 2265.78
  4622.6 2256.16  4764.8 2251.41  4805.4 2244.08  4824.5 2242.02  4937.4 2241.17
  4951.8 2237.92  4967.8 2233.97  4988.1 2233.78  4997.6 2232.13  5001.1 2229.88
  5001.6 2229.38  5016.7 2229.88  5018.8 2233.12  5039.3 2245.55  5045.6 2251.99
  5050.7 2250.34  5068.9 2262.20  5080.4 2269.75  5088.2 2277.21  5093.3 2278.98
  5100.9 2288.85  5111.2 2295.37  5136.0 2299.91  5203.6 2306.91  5268.2 2308.22
#Mann=6,-1,0
  4401.3    0.07       0  4447.3    0.16       0  4951.8    0.07       0
  5001.1    0.07       0  5016.7    0.07       0  5068.9    0.16       0
Bank Sta=5001.1,5016.7
Exp/Cntr=0.3,0.1

Type RM Length L Ch R = 1,17763,185,185,185
BEGIN DESCRIPTION:
Little Elm Creek 2 17762.729
END DESCRIPTION:
XS GIS Cut Line= 3
      1501755.00      6766738.00      1502355.27      6766771.46
      1502554.98      6766738.00
#Sta/Elev= 30
  4398.8 2279.46  4438.9 2270.29  4478.9 2264.52  4549.0 2252.43  4579.1 2250.22
  4639.2 2248.91  4671.3 2246.10  4739.3 2244.05  4779.4 2238.79  4853.8 2238.59
  4869.5 2238.13  4891.8 2230.15  4892.3 2229.65  4907.4 2230.15  4909.6 2232.13
  4919.6 2233.87  4939.6 2234.42  4979.7 2231.58  5020.0 2232.14  5040.3 2241.36
  5048.3 2248.49  5053.4 2247.58  5070.7 2268.04  5080.8 2276.08  5109.0 2285.69
  5114.0 2285.84  5131.5 2290.30  5169.6 2297.22  5192.4 2299.19  5202.5 2301.40
#Mann=4,-1,0
  4398.8    0.16       0  4853.8    0.07       0  4891.8    0.07       0
  4907.4    0.07       0
Bank Sta=4891.8,4907.4
Exp/Cntr=0.3,0.1

Type RM Length L Ch R = 1,17578,155,155,155
BEGIN DESCRIPTION:
Little Elm Creek 2 17578.18
END DESCRIPTION:
XS GIS Cut Line= 3
      1501656.98      6766938.67      1502303.76      6766942.13
      1502651.56      6766890.47
#Sta/Elev= 30
  4347.0 2296.68  4375.0 2293.05  4393.7 2288.46  4415.0 2283.16  4455.0 2268.14
  4515.0 2253.80  4545.0 2249.10  4626.8 2243.73  4675.0 2242.12  4715.0 2236.52
  4853.4 2236.94  4865.0 2237.13  4875.0 2234.76  4885.0 2228.93  4895.0 2228.76
  4955.0 2233.97  4975.0 2231.37  4984.1 2227.64  4984.6 2227.14  4999.7 2227.64
  5025.4 2230.74  5035.5 2235.22  5052.2 2246.37  5058.3 2246.15  5086.0 2270.53
  5096.1 2274.30  5187.1 2283.81  5218.9 2289.68  5247.1 2293.39  5345.4 2307.11
#Mann=9,-1,0
  4347.0    0.07       0  4393.7    0.16       0  4626.8    0.12       0
  4853.4    0.07       0  4984.1    0.07       0  4999.7    0.07       0
  5052.2   0.035       0  5218.9    0.16       0  5247.1   0.035       0
Bank Sta=4984.1,4999.7
Exp/Cntr=0.3,0.1

Type RM Length L Ch R = 1,17423,246,246,246
BEGIN DESCRIPTION:
Little Elm Creek 2 17422.64
END DESCRIPTION:
XS GIS Cut Line= 3
      1501691.59      6767097.77      1502272.63      6767080.47
      1502700.70      6767049.40
#Sta/Elev= 30
  4435.3 2290.86  4458.7 2288.37  4488.7 2282.67  4528.8 2270.71  4578.8 2258.59
  4594.7 2252.59  4605.9 2250.91  4637.0 2244.98  4678.8 2238.34  4718.8 2235.49
  4801.1 2235.24  4890.8 2236.11  4918.9 2236.25  4938.9 2234.14  4991.2 2225.27
  4991.7 2224.77  5006.8 2225.27  5049.1 2229.24  5079.1 2253.18  5089.2 2257.77
  5101.7 2260.45  5117.0 2265.35  5139.3 2270.02  5199.5 2274.15  5219.5 2272.88
  5256.3 2274.96  5269.6 2279.58  5279.3 2281.32  5359.9 2296.13  5445.8 2307.90
#Mann=9,-1,0
  4435.3    0.07       0  4605.9    0.16       0  4637.0    0.12       0
  4801.1    0.16       0  4890.8    0.07       0  4991.2    0.07       0
  5006.8    0.07       0  5101.7   0.035       0  5279.3    0.16       0
Bank Sta=4991.2,5006.8
Exp/Cntr=0.3,0.1

Type RM Length L Ch R = 1,17177,239,239,239
BEGIN DESCRIPTION:
Little Elm Creek 2 17176.84
END DESCRIPTION:
XS GIS Cut Line= 3
      1501663.91      6767274.16      1502200.00      6767312.20
      1502767.19      6767198.07
#Sta/Elev= 30
  4457.4 2279.36  4497.7 2277.83  4528.7 2276.25  4588.8 2265.88  4669.0 2261.42
  4689.1 2254.91  4699.1 2247.39  4718.8 2235.89  4723.9 2236.44  4729.2 2233.26
  4859.5 2233.28  4907.1 2231.55  4959.8 2230.65  4979.8 2227.86  4982.0 2224.65
  4982.5 2224.15  4997.6 2224.65  5043.7 2224.70  5081.5 2240.88  5089.4 2241.95
  5149.5 2242.00  5191.1 2240.71  5285.6 2247.78  5336.6 2248.84  5346.2 2251.28
  5387.6 2263.60  5408.0 2276.12  5445.3 2293.89  5496.2 2303.80  5573.4 2311.68
#Mann=7,-1,0
  4457.4    0.07       0  4497.7    0.16       0  4907.1    0.07       0
  4982.0    0.07       0  4997.6    0.07       0  5149.5   0.035       0
  5346.2    0.16       0
Bank Sta=4982,4997.6
Exp/Cntr=0.3,0.1

Type RM Length L Ch R = 1,16938,191,191,191
BEGIN DESCRIPTION:
Little Elm Creek 2 16937.69
END DESCRIPTION:
XS GIS Cut Line= 3
      1501670.85      6767609.65      1502161.95      6767533.56
      1502851.87      6767309.34
#Sta/Elev= 30
  4510.8 2275.05  4596.0 2270.81  4717.4 2258.85  4737.6 2250.27  4746.4 2238.72
  4751.5 2237.10  4757.9 2230.08  4768.0 2227.01  4923.5 2227.32  4960.2 2227.95
  4970.4 2226.93  4982.8 2222.61  4983.3 2222.11  4998.4 2222.61  5021.5 2224.30
  5053.0 2223.28  5063.5 2227.48  5071.5 2233.14  5116.1 2230.44  5172.6 2237.70
  5201.5 2238.68  5294.9 2237.41  5419.2 2240.44  5497.4 2243.84  5515.7 2247.35
  5547.2 2259.03  5610.3 2291.46  5631.3 2297.21  5662.9 2301.48  5733.2 2304.68
#Mann=6,-1,0
  4510.8    0.16       0  4923.5    0.07       0  4982.8    0.07       0
  4998.4    0.07       0  5201.5   0.035       0  5419.2    0.16       0
Bank Sta=4982.8,4998.4
Exp/Cntr=0.3,0.1

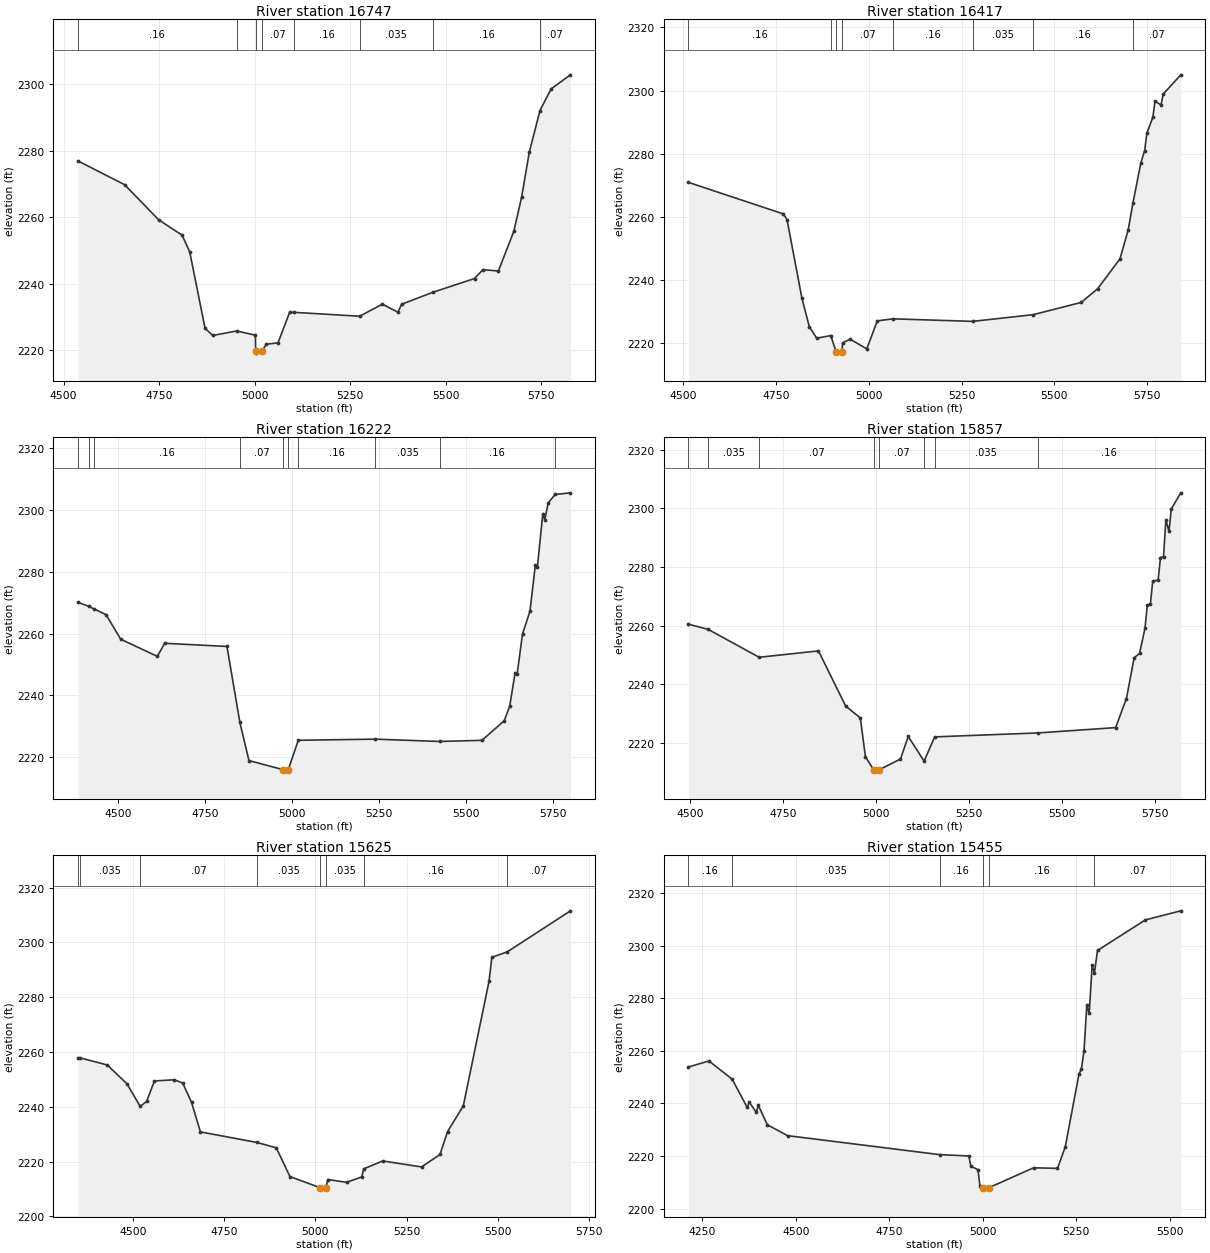
Type RM Length L Ch R = 1,16747,330,330,330
BEGIN DESCRIPTION:
Little Elm Creek 2 16746.66
END DESCRIPTION:
XS GIS Cut Line= 3
      1501643.11      6767734.16      1502106.61      6767709.95
      1502921.46      6767585.65
#Sta/Elev= 30
  4537.9 2276.96  4660.0 2269.80  4748.5 2259.28  4810.2 2254.62  4830.2 2249.55
  4870.2 2226.60  4890.3 2224.43  4952.9 2225.78  5002.0 2224.51  5002.7 2219.61
  5003.2 2219.11  5018.3 2219.61  5030.7 2221.79  5061.1 2222.21  5091.4 2231.37
  5102.8 2231.39  5274.7 2230.22  5334.2 2233.85  5374.7 2231.42  5384.8 2233.84
  5466.5 2237.44  5575.3 2241.57  5597.2 2244.24  5637.7 2243.83  5678.1 2255.77
  5698.4 2266.01  5718.6 2279.62  5746.5 2292.14  5775.9 2298.69  5826.3 2302.89
#Mann=8,-1,0
  4537.9    0.16       0  4952.9    0.07       0  5002.7    0.07       0
  5018.3    0.07       0  5102.8    0.16       0  5274.7   0.035       0
  5466.5    0.16       0  5746.5    0.07       0
Bank Sta=5002.7,5018.3
Exp/Cntr=0.3,0.1

Type RM Length L Ch R = 1,16417,195,195,195
BEGIN DESCRIPTION:
Little Elm Creek 2 16417.27
END DESCRIPTION:
XS GIS Cut Line= 3
      1501719.21      6768010.86      1502200.00      6768010.86
      1502950.28      6767620.15
#Sta/Elev= 30
  4513.9 2270.96  4769.7 2260.96  4779.7 2259.18  4819.7 2234.32  4839.7 2225.24
  4859.7 2221.59  4897.4 2222.44  4911.8 2217.37  4912.3 2216.87  4927.5 2217.37
  4929.7 2220.15  4949.7 2221.27  4994.7 2218.22  5022.9 2227.08  5065.1 2227.73
  5279.8 2226.93  5442.7 2229.04  5572.2 2232.93  5616.4 2237.24  5676.8 2246.75
  5699.1 2256.01  5711.5 2264.31  5733.2 2277.23  5743.3 2281.02  5749.0 2286.43
  5765.4 2291.63  5771.1 2296.66  5787.5 2295.47  5793.2 2298.92  5840.6 2305.01
#Mann=8,-1,0
  4513.9    0.16       0  4897.4    0.07       0  4911.8    0.07       0
  4927.5    0.07       0  5065.1    0.16       0  5279.8   0.035       0
  5442.7    0.16       0  5711.5    0.07       0
Bank Sta=4911.8,4927.5
Exp/Cntr=0.3,0.1

Type RM Length L Ch R = 1,16222,365,365,365
BEGIN DESCRIPTION:
Little Elm Creek 2 16221.93
END DESCRIPTION:
XS GIS Cut Line= 3
      1501698.48      6768360.18      1502279.55      6768166.50
      1502969.32      6767752.63
#Sta/Elev= 30
  4384.0 2270.06  4414.7 2268.81  4429.4 2267.97  4464.7 2266.10  4506.8 2258.15
  4612.2 2252.60  4633.3 2256.84  4812.5 2255.81  4849.7 2231.21  4875.8 2218.87
  4973.3 2215.96  4973.8 2215.46  4989.0 2215.96  5017.7 2225.45  5239.6 2225.81
  5424.2 2225.06  5546.3 2225.43  5610.5 2231.80  5626.0 2236.47  5641.6 2247.27
  5647.4 2246.81  5662.9 2259.84  5684.3 2267.21  5699.9 2282.19  5705.7 2281.45
  5721.3 2298.75  5727.1 2296.78  5736.8 2302.26  5756.8 2304.99  5800.9 2305.53
#Mann=10,-1,0
  4384.0   0.035       0  4414.7    0.07       0  4429.4    0.16       0
  4849.7    0.07       0  4973.3    0.07       0  4989.0    0.07       0
  5017.7    0.16       0  5239.6   0.035       0  5424.2    0.16       0
  5756.8    0.07       0
Bank Sta=4973.3,4989
Exp/Cntr=0.3,0.1

Type RM Length L Ch R = 1,15857,232,232,232
BEGIN DESCRIPTION:
Little Elm Creek 2 15856.67
END DESCRIPTION:
XS GIS Cut Line= 3
      1501968.25      6768678.39      1502417.89      6768457.02
      1502915.95      6767803.32
#Sta/Elev= 30
  4495.6 2260.47  4548.7 2258.71  4685.8 2249.19  4845.2 2251.36  4918.2 2232.55
  4957.6 2228.51  4971.3 2215.29  4993.1 2210.86  4993.6 2210.36  5008.9 2210.86
  5065.5 2214.49  5086.3 2222.19  5128.9 2213.78  5157.5 2222.04  5433.7 2223.38
  5643.4 2225.20  5672.5 2235.08  5693.3 2249.02  5707.8 2250.49  5722.4 2259.07
  5728.6 2266.97  5736.9 2267.36  5743.2 2275.13  5757.7 2275.53  5764.0 2283.16
  5772.2 2283.50  5778.5 2296.02  5786.8 2292.13  5793.1 2299.78  5818.6 2305.27
#Mann=8,-1,0
  4495.6    0.07       0  4548.7   0.035       0  4685.8    0.07       0
  4993.1    0.07       0  5008.9    0.07       0  5128.9    0.16       0
  5157.5   0.035       0  5433.7    0.16       0
Bank Sta=4993.1,5008.9
Exp/Cntr=0.3,0.1

Type RM Length L Ch R = 1,15625,170,170,170
BEGIN DESCRIPTION:
Little Elm Creek 2 15624.7
END DESCRIPTION:
XS GIS Cut Line= 3
      1502030.56      6768757.91      1502628.87      6768519.28
      1503070.81      6767970.31
#Sta/Elev= 30
  4350.2 2257.91  4354.6 2257.91  4430.3 2255.28  4484.2 2248.41  4520.5 2240.16
  4538.0 2241.99  4559.5 2249.45  4613.4 2249.87  4636.8 2248.72  4661.1 2241.68
  4685.4 2230.85  4839.9 2227.02  4893.3 2225.04  4930.6 2214.57  5013.7 2210.47
  5014.2 2209.97  5029.5 2210.47  5034.5 2213.48  5085.6 2212.44  5127.3 2214.43
  5132.6 2217.36  5184.8 2220.25  5291.3 2218.07  5341.6 2222.61  5362.4 2230.96
  5405.6 2240.39  5476.0 2285.82  5483.8 2294.59  5525.7 2296.54  5699.1 2311.54
#Mann=8,-1,0
  4350.2    0.16       0  4354.6   0.035       0  4520.5    0.07       0
  4839.9   0.035       0  5013.7   0.035       0  5029.5   0.035       0
  5132.6    0.16       0  5525.7    0.07       0
Bank Sta=5013.7,5029.5
Exp/Cntr=0.3,0.1

Type RM Length L Ch R = 1,15455,234,234,234
BEGIN DESCRIPTION:
Little Elm Creek 2 15455.34
END DESCRIPTION:
XS GIS Cut Line= 3
      1502054.71      6768861.70      1502781.05      6768571.16
      1503196.12      6768235.65
#Sta/Elev= 30
  4213.1 2253.83  4268.0 2256.14  4330.2 2249.22  4370.4 2238.47  4375.7 2240.48
  4394.6 2236.66  4400.0 2239.30  4424.2 2231.89  4478.1 2227.76  4885.2 2220.53
  4962.7 2220.03  4968.1 2216.12  4987.0 2214.86  4992.3 2208.70  4999.7 2207.93
  5000.2 2207.43  5015.6 2207.93  5135.6 2215.54  5199.5 2215.32  5220.3 2223.45
  5257.0 2251.17  5263.5 2253.13  5270.5 2259.99  5277.9 2277.32  5284.3 2274.18
  5292.2 2292.43  5298.3 2289.65  5306.6 2298.15  5434.5 2309.75  5529.1 2313.20
#Mann=6,-1,0
  4213.1    0.16       0  4330.2   0.035       0  4885.2    0.16       0
  4999.7    0.07       0  5015.6    0.16       0  5298.3    0.07       0
Bank Sta=4999.7,5015.6
Exp/Cntr=0.3,0.1