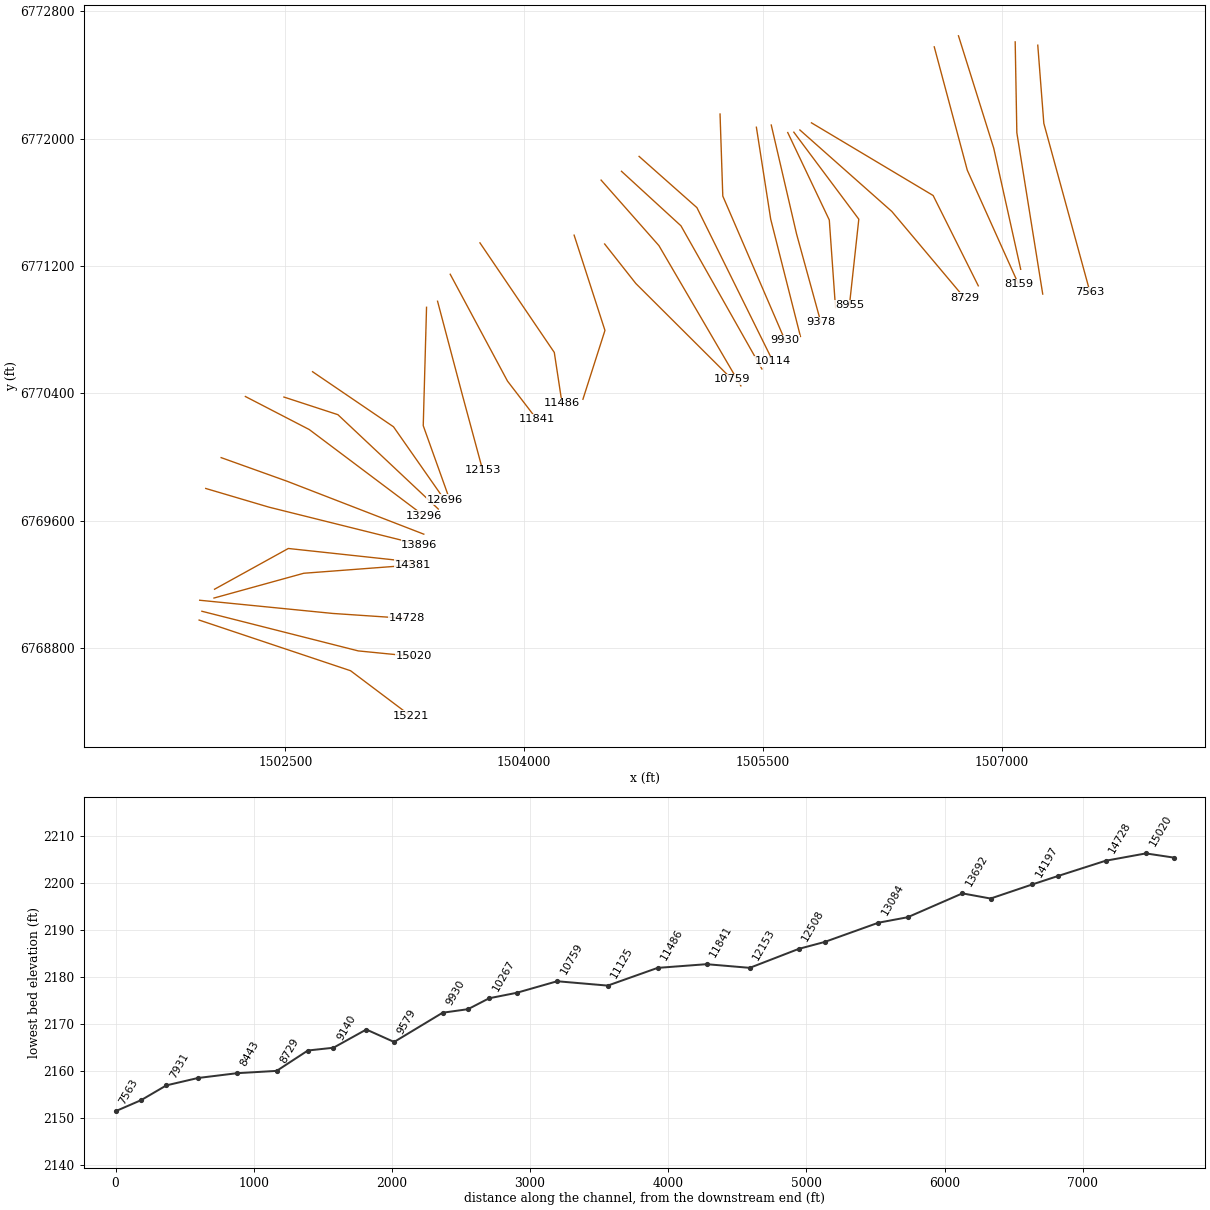
HEC-RAS study Little Elm Creek 2.prj: Little Elm Creek 2 Base Level Engineering

--- Little Elm Creek 2.g01 (geometry) --- (continued)

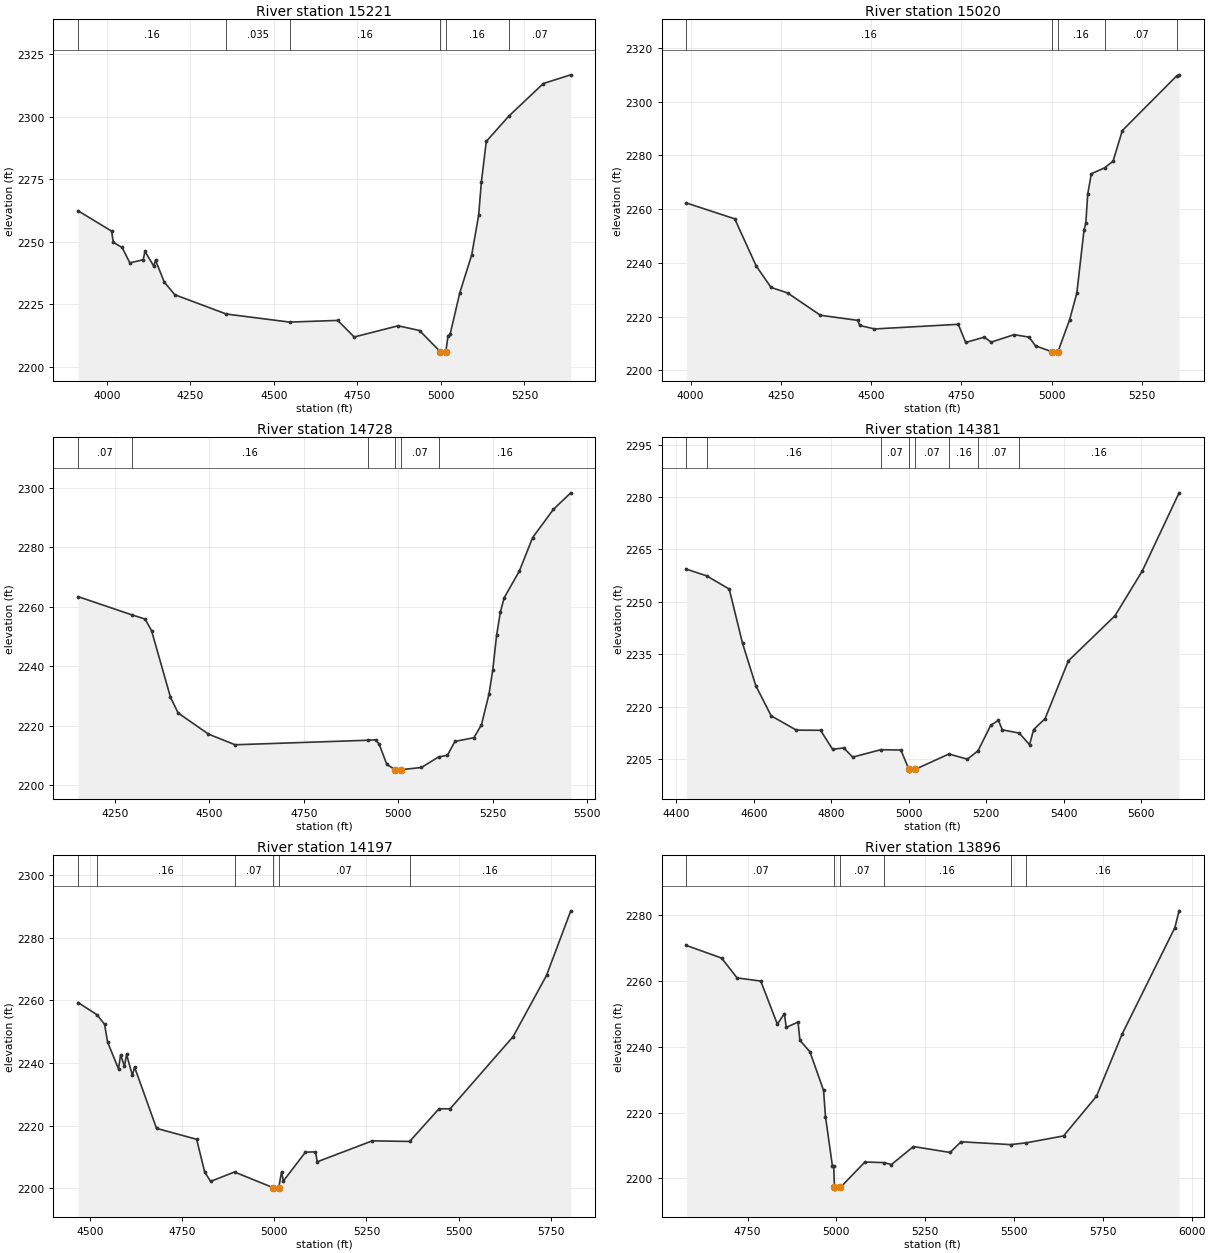
Type RM Length L Ch R = 1,15221,201,201,201
BEGIN DESCRIPTION:
Little Elm Creek 2 15220.84
END DESCRIPTION:
XS GIS Cut Line= 3
      1501957.91      6768975.82      1502909.02      6768657.63
      1503286.03      6768374.01
#Sta/Elev= 30
  3914.1 2262.37  4014.4 2254.26  4019.6 2249.77  4045.9 2247.73  4069.2 2241.55
  4109.1 2242.82  4114.4 2246.19  4140.7 2240.26  4146.0 2242.58  4172.3 2233.85
  4203.8 2228.83  4357.9 2221.12  4547.1 2217.90  4691.3 2218.57  4740.6 2211.95
  4872.2 2216.42  4936.1 2214.53  4998.9 2206.00  4999.4 2205.50  5014.9 2206.00
  5021.4 2212.44  5027.7 2213.00  5056.8 2229.65  5092.3 2244.71  5113.1 2260.53
  5121.4 2274.00  5136.0 2290.09  5203.2 2300.17  5306.7 2313.22  5388.8 2316.69
#Mann=6,-1,0
  3914.1    0.16       0  4357.9   0.035       0  4547.1    0.16       0
  4998.9    0.07       0  5014.9    0.16       0  5203.2    0.07       0
Bank Sta=4998.9,5014.9
Exp/Cntr=0.3,0.1

Type RM Length L Ch R = 1,15020,292,292,292
BEGIN DESCRIPTION:
Little Elm Creek 2 15020.201
END DESCRIPTION:
XS GIS Cut Line= 3
      1501975.19      6769031.16      1502957.44      6768782.14
      1503306.81      6768747.55
#Sta/Elev= 30
  3988.2 2262.30  4122.1 2256.39  4181.5 2238.86  4222.5 2230.87  4268.6 2228.79
  4359.4 2220.49  4462.6 2218.59  4468.4 2216.70  4509.0 2215.39  4741.1 2217.12
  4761.7 2210.36  4813.3 2212.34  4832.0 2210.47  4895.8 2213.27  4937.1 2212.35
  4955.0 2209.10  5001.1 2206.89  5001.6 2206.39  5017.1 2206.89  5049.3 2218.76
  5069.4 2228.71  5089.4 2252.26  5094.4 2254.92  5099.6 2265.61  5109.6 2273.19
  5146.2 2275.36  5169.9 2277.88  5195.4 2289.26  5345.6 2309.57  5352.6 2310.01
#Mann=5,-1,0
  3988.2    0.16       0  5001.1    0.07       0  5017.1    0.16       0
  5146.2    0.07       0  5345.6    0.16       0
Bank Sta=5001.1,5017.1
Exp/Cntr=0.3,0.1

Type RM Length L Ch R = 1,14728,347,347,347
BEGIN DESCRIPTION:
Little Elm Creek 2 14728.42
END DESCRIPTION:
XS GIS Cut Line= 3
      1501961.36      6769100.33      1502798.35      6769017.33
      1503260.92      6768986.26
#Sta/Elev= 30
  4152.2 2263.47  4294.2 2257.36  4329.8 2255.93  4346.8 2252.04  4397.0 2229.65
  4417.1 2224.37  4497.5 2217.27  4567.9 2213.68  4920.3 2215.20  4940.3 2215.35
  4949.7 2213.87  4969.8 2207.08  4992.0 2205.32  4992.5 2204.82  5008.0 2205.32
  5061.5 2206.04  5106.8 2209.59  5130.2 2210.13  5150.3 2214.82  5200.4 2216.05
  5220.5 2220.42  5240.5 2230.78  5250.5 2238.93  5260.5 2250.43  5270.6 2258.30
  5280.6 2263.09  5320.7 2272.03  5356.0 2283.32  5410.9 2292.79  5456.9 2298.35
#Mann=6,-1,0
  4152.2    0.07       0  4294.2    0.16       0  4920.3    0.07       0
  4992.0    0.07       0  5008.0    0.07       0  5106.8    0.16       0
Bank Sta=4992,5008
Exp/Cntr=0.3,0.1

Type RM Length L Ch R = 1,14381,184,184,184
BEGIN DESCRIPTION:
Little Elm Creek 2 14380.95
END DESCRIPTION:
XS GIS Cut Line= 3
      1502051.23      6769114.16      1502615.04      6769269.81
      1503299.87      6769321.69
#Sta/Elev= 30
  4425.9 2259.34  4478.1 2257.43  4536.5 2253.64  4570.9 2238.11  4605.2 2225.96
  4644.7 2217.37  4709.9 2213.27  4772.2 2213.23  4803.3 2207.78  4832.1 2208.18
  4855.2 2205.55  4927.6 2207.67  4979.6 2207.58  5000.2 2202.04  5000.7 2201.54
  5016.2 2202.04  5103.6 2206.44  5151.2 2204.96  5178.7 2207.37  5211.3 2214.63
  5231.4 2216.07  5241.4 2213.36  5285.2 2212.42  5311.6 2209.10  5322.2 2213.43
  5351.7 2216.57  5411.9 2233.10  5532.3 2246.02  5602.5 2258.79  5697.6 2281.18
#Mann=8,-1,0
  4425.9    0.07       0  4478.1    0.16       0  4927.6    0.07       0
  5000.2    0.07       0  5016.2    0.07       0  5103.6    0.16       0
  5178.7    0.07       0  5285.2    0.16       0
Bank Sta=5000.2,5016.2
Exp/Cntr=0.3,0.1

Type RM Length L Ch R = 1,14197,301,301,301
BEGIN DESCRIPTION:
Little Elm Creek 2 14197.28
END DESCRIPTION:
XS GIS Cut Line= 3
      1502054.75      6769169.52      1502518.19      6769425.45
      1503320.34      6769339.01
#Sta/Elev= 30
  4467.9 2259.26  4519.2 2255.38  4539.8 2252.33  4548.1 2246.62  4577.6 2238.11
  4583.3 2242.58  4593.7 2238.99  4599.4 2242.71  4615.4 2236.02  4621.1 2238.71
  4680.7 2219.15  4789.6 2215.64  4811.3 2205.22  4827.4 2202.23  4892.2 2205.22
  4996.2 2200.26  4996.7 2199.76  5012.2 2200.26  5019.7 2205.23  5024.8 2202.36
  5084.6 2211.56  5111.7 2211.64  5116.7 2208.48  5265.7 2215.15  5367.2 2214.97
  5446.7 2225.38  5476.9 2225.38  5647.9 2248.42  5738.4 2267.92  5804.1 2288.51
#Mann=6,-1,0
  4467.9    0.07       0  4519.2    0.16       0  4892.2    0.07       0
  4996.2    0.07       0  5012.2    0.07       0  5367.2    0.16       0
Bank Sta=4996.2,5012.2
Exp/Cntr=0.3,0.1

Type RM Length L Ch R = 1,13896,204,204,204
BEGIN DESCRIPTION:
Little Elm Creek 2 13896.2
END DESCRIPTION:
XS GIS Cut Line= 3
      1501999.44      6769802.43      1502397.14      6769684.85
      1503340.69      6769449.83
#Sta/Elev= 30
  4577.6 2270.70  4676.7 2266.88  4720.4 2260.85  4787.0 2259.89  4833.7 2246.84
  4853.5 2250.00  4858.8 2245.84  4892.0 2247.46  4897.2 2241.92  4925.3 2238.45
  4963.8 2226.73  4969.2 2218.79  4988.6 2203.90  4992.3 2203.90  4994.5 2197.26
  4995.0 2196.76  5011.0 2197.26  5080.2 2204.99  5132.9 2204.81  5155.0 2204.23
  5216.8 2209.68  5319.9 2207.89  5350.8 2211.13  5490.9 2210.27  5535.0 2210.82
  5639.4 2212.90  5732.1 2224.94  5804.3 2243.79  5952.6 2276.05  5964.7 2281.21
#Mann=6,-1,0
  4577.6    0.07       0  4994.5    0.07       0  5011.0    0.07       0
  5132.9    0.16       0  5490.9    0.07       0  5535.0    0.16       0
Bank Sta=4994.5,5011
Exp/Cntr=0.3,0.1

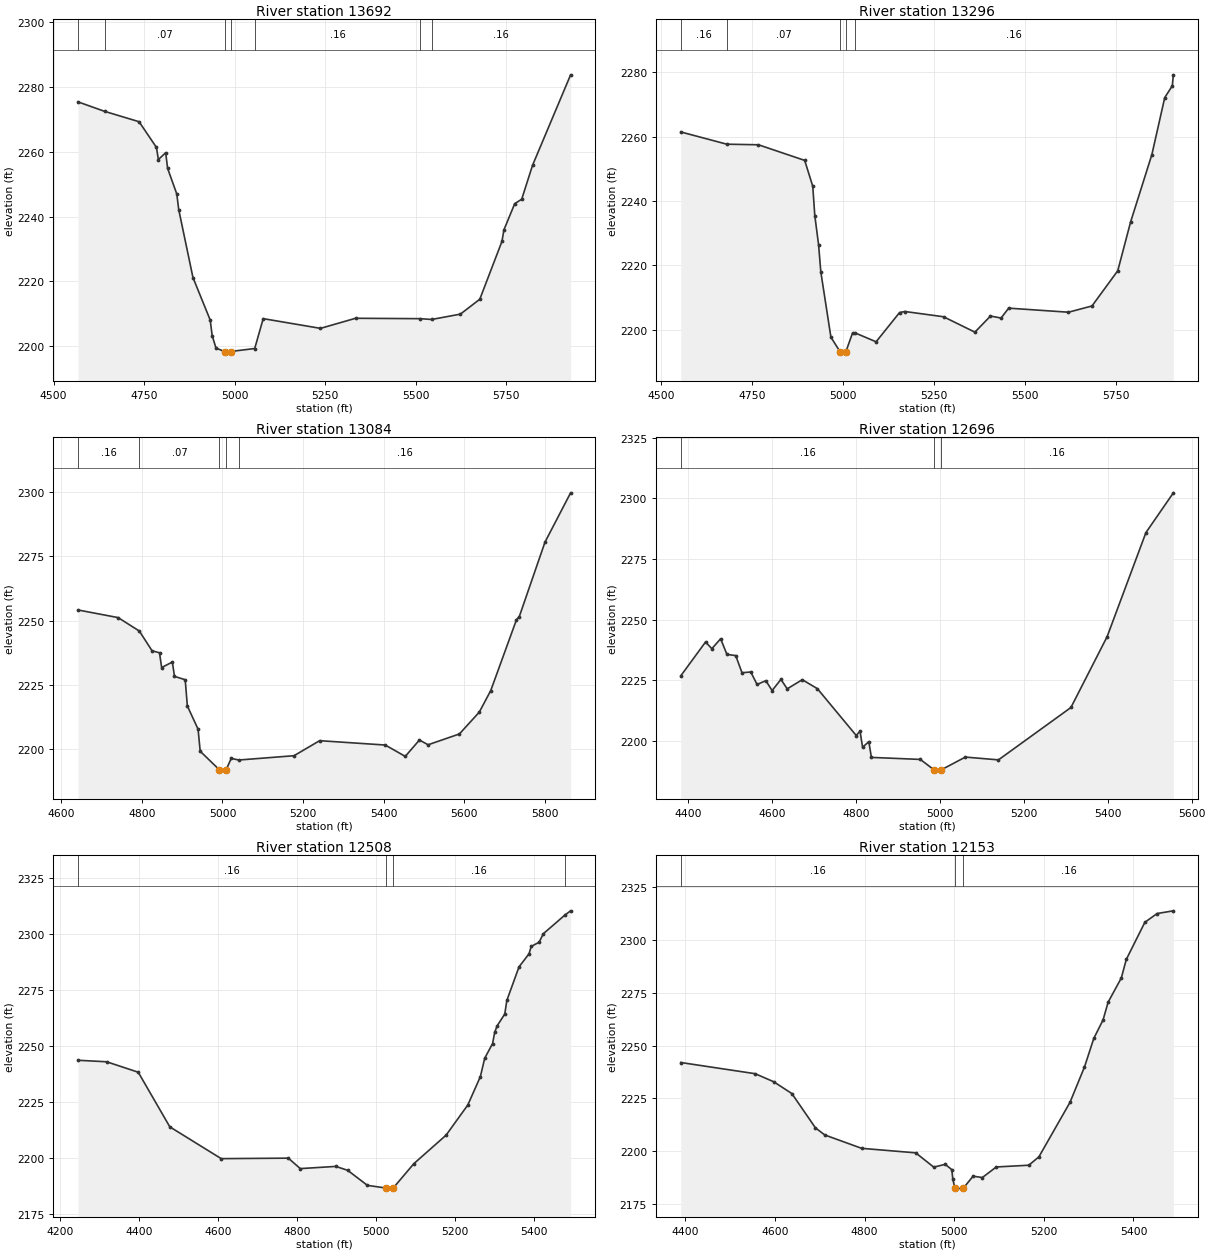
Type RM Length L Ch R = 1,13692,396,396,396
BEGIN DESCRIPTION:
Little Elm Creek 2 13692.31
END DESCRIPTION:
XS GIS Cut Line= 3
      1502096.25      6769996.13      1502511.28      6769847.41
      1503368.99      6769515.39
#Sta/Elev= 30
  4567.7 2275.37  4641.4 2272.44  4736.3 2269.25  4784.3 2261.32  4789.6 2257.58
  4809.8 2259.69  4815.1 2254.86  4840.5 2246.95  4845.8 2242.15  4885.1 2221.19
  4932.8 2208.06  4938.2 2203.26  4948.8 2199.41  4972.4 2198.36  4972.9 2197.86
  4988.9 2198.36  5055.7 2199.28  5079.2 2208.50  5237.4 2205.50  5334.3 2208.61
  5513.1 2208.49  5544.3 2208.24  5623.8 2209.89  5677.4 2214.48  5738.7 2232.35
  5744.1 2235.89  5774.0 2243.99  5793.2 2245.33  5823.1 2255.79  5928.3 2283.72
#Mann=7,-1,0
  4567.7    0.16       0  4641.4    0.07       0  4972.4    0.07       0
  4988.9    0.07       0  5055.7    0.16       0  5513.1    0.07       0
  5544.3    0.16       0
Bank Sta=4972.4,4988.9
Exp/Cntr=0.3,0.1

Type RM Length L Ch R = 1,13296,212,212,212
BEGIN DESCRIPTION:
Little Elm Creek 2 13296.45
END DESCRIPTION:
XS GIS Cut Line= 3
      1502248.45      6770380.03      1502649.62      6770172.52
      1503371.24      6769630.45
#Sta/Elev= 30
  4554.1 2261.42  4680.6 2257.62  4767.5 2257.44  4894.7 2252.59  4916.9 2244.56
  4922.5 2235.48  4933.0 2226.33  4939.0 2218.02  4966.8 2197.72  4991.6 2193.27
  4992.1 2192.77  5008.1 2193.27  5026.4 2199.04  5033.6 2199.03  5091.0 2196.29
  5155.6 2205.37  5170.1 2205.69  5276.4 2204.06  5362.7 2199.28  5405.5 2204.28
  5434.7 2203.66  5455.5 2206.73  5620.0 2205.47  5684.6 2207.41  5755.4 2218.33
  5790.8 2233.50  5849.2 2254.39  5884.6 2272.08  5905.4 2275.75  5908.3 2279.15
#Mann=5,-1,0
  4554.1    0.16       0  4680.6    0.07       0  4991.6    0.07       0
  5008.1    0.07       0  5033.6    0.16       0
Bank Sta=4991.6,5008.1
Exp/Cntr=0.3,0.1

Type RM Length L Ch R = 1,13084,388,388,388
BEGIN DESCRIPTION:
Little Elm Creek 2 13083.7
END DESCRIPTION:
XS GIS Cut Line= 3
      1502490.48      6770376.60      1502829.47      6770265.91
      1503460.13      6769673.16
#Sta/Elev= 30
  4641.6 2254.10  4741.0 2251.15  4793.6 2245.94  4825.2 2238.29  4843.7 2237.50
  4849.0 2231.78  4875.6 2233.91  4880.9 2228.35  4907.5 2227.04  4912.8 2216.87
  4939.4 2207.87  4944.7 2199.31  4992.4 2192.10  4992.9 2191.60  5008.9 2192.10
  5021.7 2196.53  5040.5 2195.91  5177.5 2197.58  5241.0 2203.41  5403.8 2201.72
  5453.5 2197.32  5488.6 2203.67  5510.1 2201.82  5587.8 2206.02  5637.1 2214.48
  5665.5 2222.83  5729.4 2250.32  5736.3 2251.50  5800.2 2280.45  5863.7 2299.54
#Mann=5,-1,0
  4641.6    0.16       0  4793.6    0.07       0  4992.4    0.07       0
  5008.9    0.07       0  5040.5    0.16       0
Bank Sta=4992.4,5008.9
Exp/Cntr=0.3,0.1

Type RM Length L Ch R = 1,12696,188,188,188
BEGIN DESCRIPTION:
Little Elm Creek 2 12696.17
END DESCRIPTION:
XS GIS Cut Line= 3
      1502670.41      6770535.66      1503178.80      6770189.82
      1503499.09      6769731.76
#Sta/Elev= 30
  4382.6 2226.81  4441.6 2240.76  4456.6 2238.00  4477.5 2242.09  4492.5 2235.64
  4513.5 2235.15  4528.4 2228.08  4549.4 2228.38  4564.3 2223.25  4585.3 2224.79
  4600.2 2220.72  4621.2 2225.33  4636.2 2221.44  4672.1 2225.21  4708.0 2221.52
  4800.8 2202.17  4809.7 2204.02  4815.8 2197.35  4830.7 2199.65  4836.8 2193.16
  4953.4 2192.33  4986.4 2188.00  4986.9 2187.50  5002.9 2188.00  5060.7 2193.29
  5139.6 2192.14  5312.3 2213.74  5398.6 2242.97  5491.0 2285.87  5556.4 2302.27
#Mann=3,-1,0
  4382.6    0.16       0  4986.4    0.07       0  5002.9    0.16       0
Bank Sta=4986.4,5002.9
Exp/Cntr=0.3,0.1

Type RM Length L Ch R = 1,12508,355,355,355
BEGIN DESCRIPTION:
Little Elm Creek 2 12507.51
END DESCRIPTION:
XS GIS Cut Line= 3
      1503386.32      6770940.34      1503365.57      6770196.73
      1503535.03      6769722.93
#Sta/Elev= 30
  4246.2 2243.59  4318.6 2242.92  4398.6 2238.25  4478.6 2213.84  4608.7 2199.64
  4778.7 2199.86  4808.8 2195.19  4898.8 2196.17  4928.8 2194.43  4978.8 2187.71
  5025.2 2186.52  5025.7 2186.02  5044.2 2186.52  5096.3 2197.38  5178.0 2210.13
  5233.0 2223.60  5264.9 2236.32  5275.7 2244.46  5295.8 2251.08  5301.1 2256.12
  5307.4 2259.01  5326.6 2264.24  5331.9 2270.35  5362.7 2285.33  5388.1 2291.17
  5393.5 2294.44  5413.6 2296.34  5424.2 2300.13  5478.8 2308.46  5493.3 2310.36
#Mann=4,-1,0
  4246.2    0.16       0  5025.2    0.07       0  5044.2    0.16       0
  5478.8    0.07       0
Bank Sta=5025.2,5044.2
Exp/Cntr=0.3,0.1

Type RM Length L Ch R = 1,12153,312,312,312
BEGIN DESCRIPTION:
Little Elm Creek 2 12153.23
END DESCRIPTION:
XS GIS Cut Line= 3
      1503455.50      6770978.38      1503611.13      6770390.42
      1503739.10      6769916.60
#Sta/Elev= 30
  4390.0 2241.96  4555.9 2236.66  4597.3 2232.85  4637.8 2227.25  4690.4 2211.01
  4711.1 2207.64  4793.5 2201.30  4914.2 2199.16  4954.4 2192.39  4980.0 2193.72
  4994.7 2191.20  4996.9 2186.70  5001.6 2182.47  5002.1 2181.97  5020.6 2182.47
  5042.1 2188.10  5062.9 2187.47  5093.9 2192.47  5166.4 2193.30  5189.0 2197.27
  5258.4 2223.10  5290.7 2239.84  5311.5 2253.40  5332.2 2262.17  5343.4 2270.52
  5372.9 2282.03  5384.0 2290.81  5425.4 2308.39  5452.7 2312.55  5489.0 2313.83
#Mann=3,-1,0
  4390.0    0.16       0  5001.6    0.07       0  5020.6    0.16       0
Bank Sta=5001.6,5020.6
Exp/Cntr=0.3,0.1

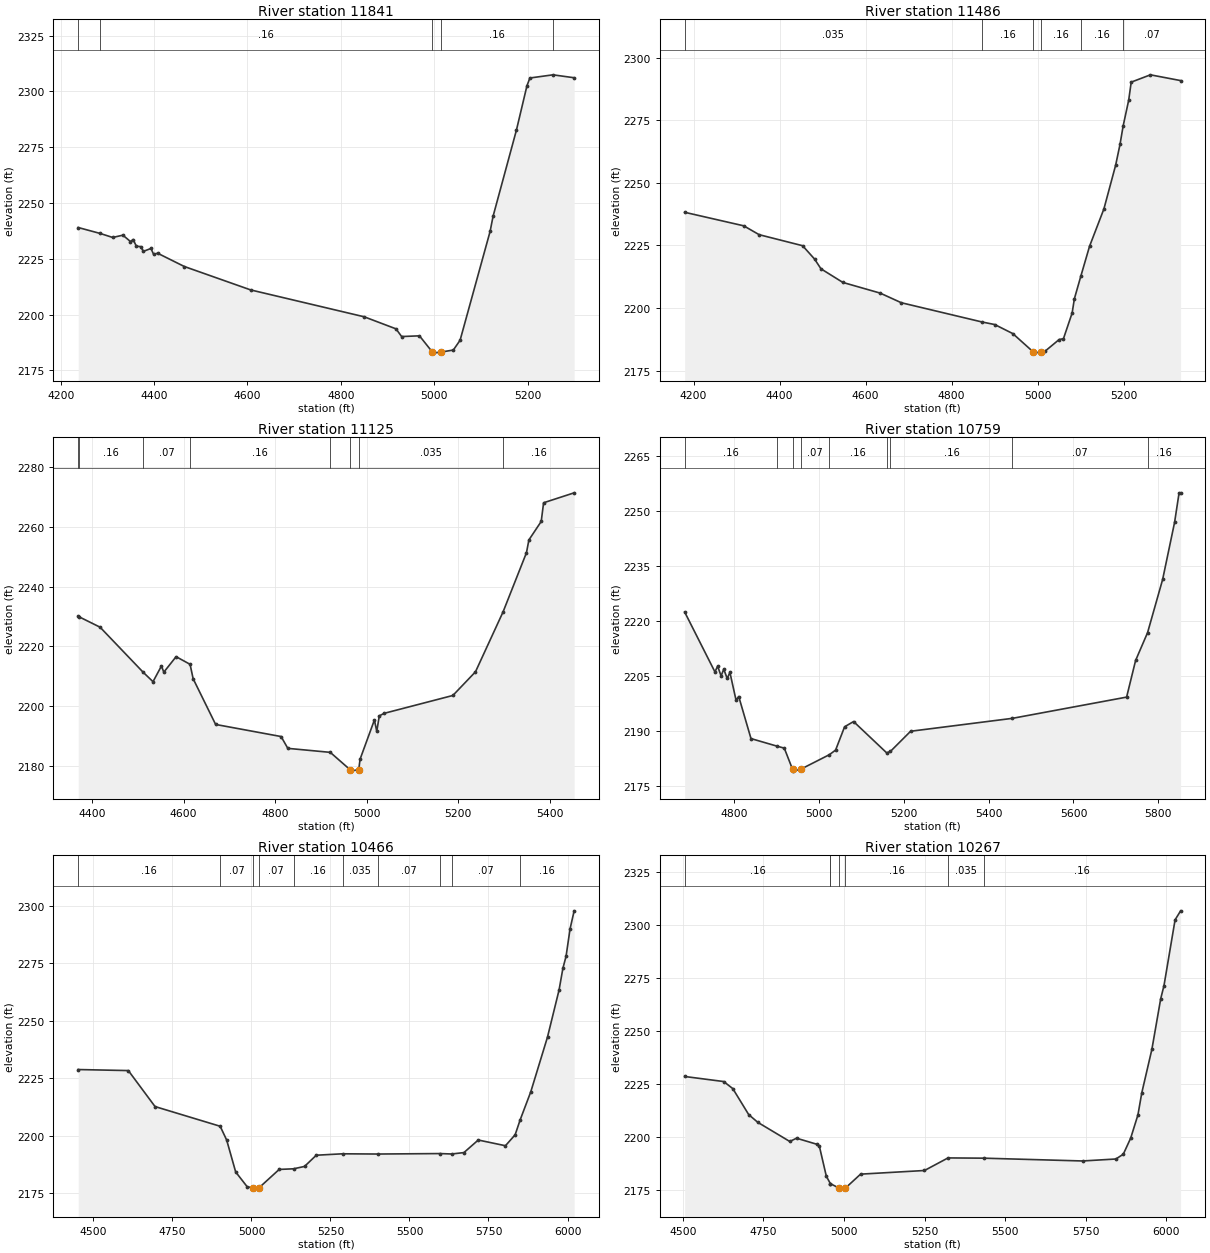
Type RM Length L Ch R = 1,11841,355,355,355
BEGIN DESCRIPTION:
Little Elm Creek 2 11841.41
END DESCRIPTION:
XS GIS Cut Line= 3
      1503535.06      6771147.83      1503894.74      6770476.89
      1504078.05      6770238.24
#Sta/Elev= 30
  4237.5 2239.03  4284.6 2236.37  4311.3 2234.58  4333.2 2235.60  4349.4 2232.75
  4355.1 2233.66  4362.1 2230.64  4371.4 2230.48  4377.0 2228.34  4393.3 2229.65
  4399.0 2227.02  4407.5 2227.52  4464.8 2221.56  4606.9 2211.07  4850.0 2199.03
  4918.1 2193.63  4930.2 2190.18  4968.4 2190.50  4996.0 2183.25  4996.5 2182.75
  5015.0 2183.25  5040.9 2184.13  5055.4 2188.52  5119.7 2237.30  5126.0 2244.03
  5175.9 2282.53  5198.6 2302.54  5204.9 2306.03  5254.4 2307.45  5299.7 2306.14
#Mann=5,-1,0
  4237.5    0.07       0  4284.6    0.16       0  4996.0    0.07       0
  5015.0    0.16       0  5254.4    0.07       0
Bank Sta=4996,5015
Exp/Cntr=0.3,0.1

Type RM Length L Ch R = 1,11486,361,361,361
BEGIN DESCRIPTION:
Little Elm Creek 2 11486.01
END DESCRIPTION:
XS GIS Cut Line= 3
      1503721.83      6771344.99      1504188.73      6770656.74
      1504237.15      6770338.58
#Sta/Elev= 30
  4179.2 2238.20  4316.5 2232.80  4352.4 2229.26  4453.5 2224.85  4481.2 2219.54
  4496.2 2215.63  4547.1 2210.19  4633.9 2205.93  4683.1 2202.08  4870.4 2194.41
  4900.4 2193.37  4942.4 2189.76  4989.8 2182.46  4990.3 2181.96  5008.8 2182.46
  5017.0 2182.67  5050.1 2187.38  5060.2 2187.73  5080.4 2197.99  5085.6 2203.67
  5100.4 2212.57  5120.9 2224.64  5154.3 2239.56  5181.6 2257.02  5191.7 2265.28
  5199.0 2272.66  5211.9 2282.95  5217.8 2290.17  5262.5 2293.09  5332.7 2290.79
#Mann=6,-1,0
  4179.2   0.035       0  4870.4    0.16       0  4989.8    0.07       0
  5008.8    0.16       0  5100.4    0.16       0  5199.0    0.07       0
Bank Sta=4989.8,5008.8
Exp/Cntr=0.3,0.1

Type RM Length L Ch R = 1,11125,366,366,366
BEGIN DESCRIPTION:
Little Elm Creek 2 11124.51
END DESCRIPTION:
XS GIS Cut Line= 3
      1504313.26      6771393.40      1504506.93      6770795.08
      1504368.61      6770362.85
#Sta/Elev= 30
  4370.1 2230.09  4372.0 2229.89  4417.8 2226.41  4512.2 2211.26  4533.4 2208.15
  4551.8 2213.41  4557.0 2211.34  4583.8 2216.53  4614.3 2213.97  4621.0 2209.14
  4670.1 2193.82  4813.0 2189.77  4827.7 2185.81  4920.4 2184.47  4963.5 2178.68
  4964.0 2178.18  4982.6 2178.68  4985.4 2182.16  5016.7 2195.31  5021.9 2191.52
  5027.4 2196.69  5037.9 2197.54  5188.0 2203.53  5237.4 2211.46  5297.6 2231.53
  5348.7 2251.37  5354.0 2255.65  5380.9 2261.84  5386.1 2268.10  5452.8 2271.43
#Mann=8,-1,0
  4370.1    0.07       0  4372.0    0.16       0  4512.2    0.07       0
  4614.3    0.16       0  4920.4   0.035       0  4963.5   0.035       0
  4982.6   0.035       0  5297.6    0.16       0
Bank Sta=4963.5,4982.6
Exp/Cntr=0.3,0.1

Type RM Length L Ch R = 1,10759,293,293,293
BEGIN DESCRIPTION:
Little Elm Creek 2 10758.632
END DESCRIPTION:
XS GIS Cut Line= 3
      1504505.02      6771337.98      1504700.96      6771089.67
      1505305.02      6770487.98
#Sta/Elev= 30
  4683.7 2222.53  4755.0 2206.19  4761.4 2207.75  4769.5 2205.09  4775.8 2206.93
  4783.9 2204.40  4790.3 2206.06  4804.7 2198.50  4811.1 2199.47  4840.0 2187.99
  4900.3 2185.96  4918.5 2185.38  4937.9 2179.61  4938.4 2179.11  4957.0 2179.61
  5024.8 2183.60  5039.4 2184.85  5060.6 2191.21  5081.8 2192.64  5159.9 2184.09
  5168.8 2184.51  5216.2 2189.99  5456.3 2193.52  5725.3 2199.31  5746.5 2209.31
  5774.7 2216.90  5810.2 2231.41  5838.4 2247.01  5849.0 2255.06  5852.6 2255.06
#Mann=9,-1,0
  4683.7    0.16       0  4900.3    0.07       0  4937.9    0.07       0
  4957.0    0.07       0  5024.8    0.16       0  5159.9   0.035       0
  5168.8    0.16       0  5456.3    0.07       0  5774.7    0.16       0
Bank Sta=4937.9,4957
Exp/Cntr=0.3,0.1

Type RM Length L Ch R = 1,10466,199,199,199
BEGIN DESCRIPTION:
Little Elm Creek 2 10466.35
END DESCRIPTION:
XS GIS Cut Line= 3
      1504482.74      6771739.28      1504845.88      6771327.72
      1505360.59      6770446.84
#Sta/Elev= 30
  4451.9 2228.77  4610.5 2228.32  4695.0 2212.63  4901.1 2204.04  4921.7 2198.00
  4950.1 2184.12  4986.1 2177.75  5003.4 2177.14  5003.9 2176.64  5023.3 2177.14
  5087.8 2185.23  5133.2 2185.50  5167.9 2186.53  5205.1 2191.42  5288.1 2192.04
  5399.8 2191.94  5596.1 2192.14  5633.6 2191.96  5672.2 2192.57  5717.6 2198.05
  5803.6 2195.56  5834.3 2200.33  5850.0 2206.77  5883.8 2219.08  5936.7 2242.95
  5973.3 2263.47  5985.4 2272.90  5995.4 2278.14  6008.1 2290.13  6021.0 2297.96
#Mann=10,-1,0
  4451.9    0.16       0  4901.1    0.07       0  5003.4    0.07       0
  5023.3    0.07       0  5133.2    0.16       0  5288.1   0.035       0
  5399.8    0.07       0  5596.1    0.16       0  5633.6    0.07       0
  5850.0    0.16       0
Bank Sta=5003.4,5023.3
Exp/Cntr=0.3,0.1

Type RM Length L Ch R = 1,10267,153,153,153
BEGIN DESCRIPTION:
Little Elm Creek 2 10266.53
END DESCRIPTION:
XS GIS Cut Line= 3
      1504610.69      6771794.64      1504984.22      6771452.23
      1505492.62      6770553.03
#Sta/Elev= 30
  4505.4 2228.57  4626.4 2226.19  4654.8 2222.86  4704.1 2210.62  4732.4 2206.96
  4831.7 2197.94  4852.7 2199.48  4916.8 2196.58  4923.6 2195.68  4945.2 2181.54
  4957.8 2178.06  4957.9 2178.05  4984.6 2175.98  4985.1 2175.48  5004.5 2175.98
  5051.5 2182.54  5249.9 2184.26  5323.0 2190.19  5433.8 2190.07  5740.7 2188.75
  5844.1 2189.68  5867.1 2191.93  5890.1 2199.52  5912.6 2210.48  5924.5 2220.84
  5955.9 2241.37  5983.3 2265.22  5993.4 2271.35  6027.9 2302.39  6045.1 2306.65
#Mann=7,-1,0
  4505.4    0.16       0  4957.8    0.07       0  4957.9    0.16       0
  4984.6    0.07       0  5004.5    0.16       0  5323.0   0.035       0
  5433.8    0.16       0
Bank Sta=4984.6,5004.5
Exp/Cntr=0.3,0.1

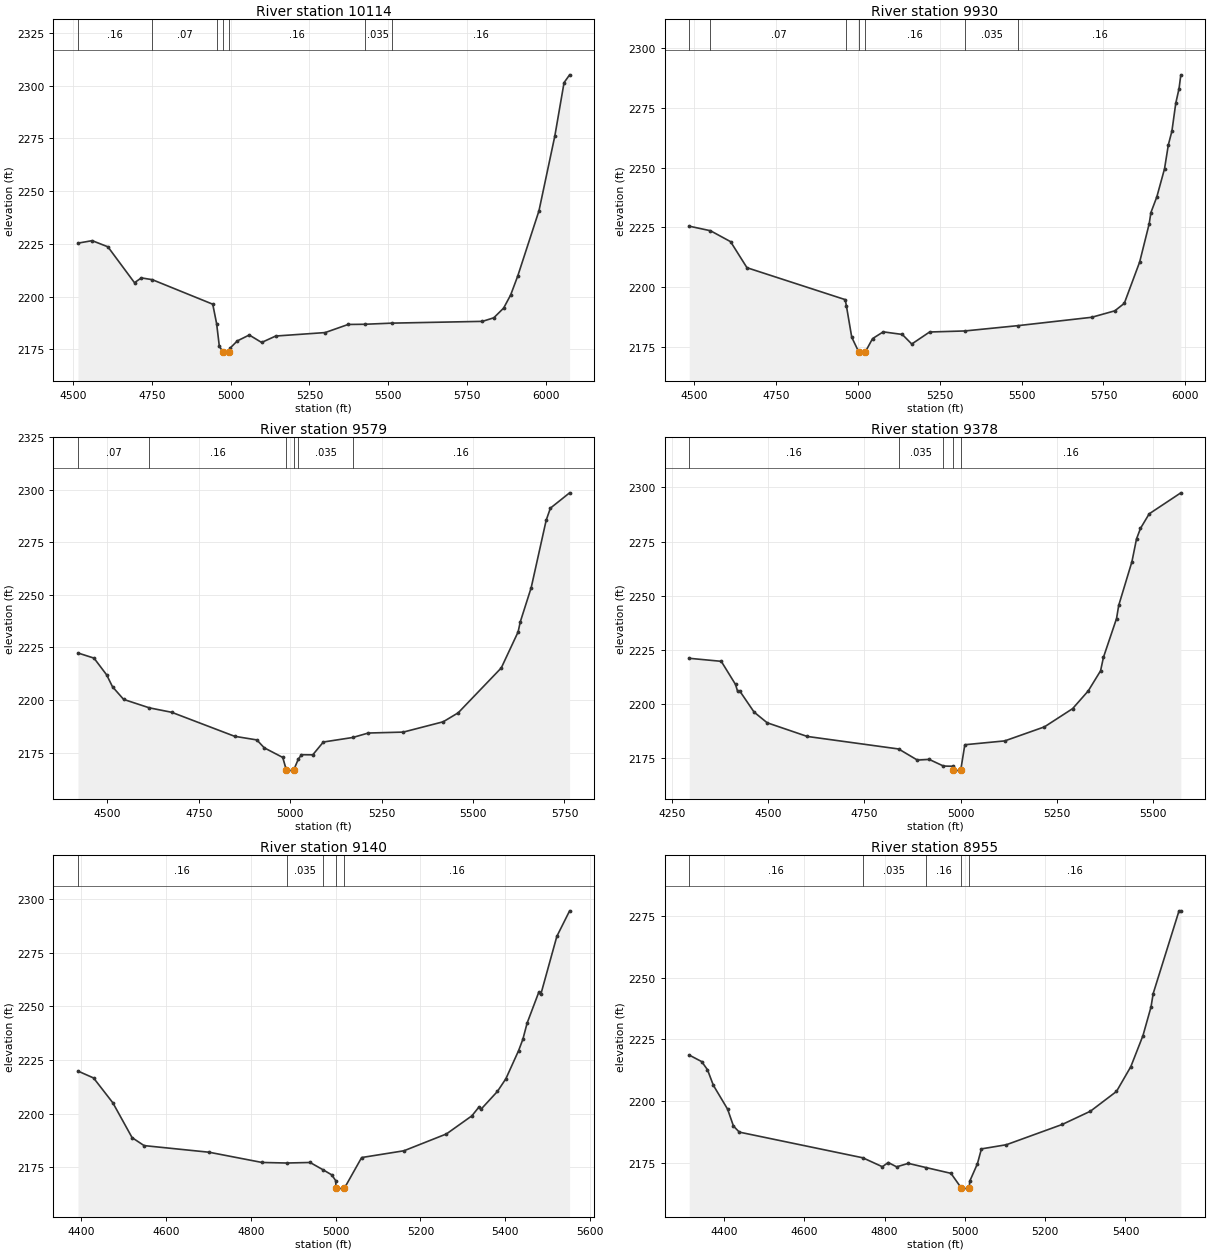
Type RM Length L Ch R = 1,10114,184,184,184
BEGIN DESCRIPTION:
Little Elm Creek 2 10114.37
END DESCRIPTION:
XS GIS Cut Line= 3
      1504721.34      6771888.05      1505084.53      6771566.37
      1505561.41      6770602.23
#Sta/Elev= 30
  4515.1 2225.33  4560.1 2226.50  4610.0 2223.59  4694.5 2206.55  4716.2 2208.84
  4751.1 2207.99  4942.9 2196.36  4955.2 2187.14  4963.8 2176.43  4975.6 2173.65
  4976.1 2173.15  4995.6 2173.65  4997.2 2175.40  5020.8 2178.94  5058.8 2181.75
  5098.1 2178.21  5142.9 2181.26  5299.7 2182.90  5372.8 2186.75  5425.4 2186.84
  5512.3 2187.38  5799.1 2188.22  5835.2 2189.91  5866.4 2194.51  5888.8 2200.77
  5911.3 2209.77  5978.6 2240.67  6029.0 2276.17  6058.3 2301.48  6075.9 2305.17
#Mann=7,-1,0
  4515.1    0.16       0  4751.1    0.07       0  4955.2    0.16       0
  4975.6    0.07       0  4995.6    0.16       0  5425.4   0.035       0
  5512.3    0.16       0
Bank Sta=4975.6,4995.6
Exp/Cntr=0.3,0.1

Type RM Length L Ch R = 1,9930,351,351,351
BEGIN DESCRIPTION:
Little Elm Creek 2 9929.6
END DESCRIPTION:
XS GIS Cut Line= 3
      1505229.79      6772154.38      1505247.08      6771639.00
      1505637.86      6770732.94
#Sta/Elev= 30
  4484.0 2225.51  4549.0 2223.60  4610.4 2219.03  4660.5 2208.13  4960.6 2194.78
  4964.3 2192.22  4980.7 2179.03  5002.1 2172.89  5002.6 2172.39  5022.1 2172.89
  5044.3 2178.47  5077.0 2181.29  5135.1 2180.21  5164.1 2176.20  5218.6 2181.23
  5326.5 2181.67  5488.7 2183.89  5714.1 2187.39  5784.6 2190.09  5813.6 2193.22
  5860.6 2210.53  5889.6 2226.46  5895.0 2231.23  5913.1 2237.80  5936.6 2249.55
  5948.2 2259.52  5959.1 2265.28  5971.0 2277.02  5980.9 2283.08  5986.4 2288.84
#Mann=7,-1,0
  4484.0    0.16       0  4549.0    0.07       0  4964.3    0.16       0
  5002.1    0.07       0  5022.1    0.16       0  5326.5   0.035       0
  5488.7    0.16       0
Bank Sta=5002.1,5022.1
Exp/Cntr=0.3,0.1

Type RM Length L Ch R = 1,9579,201,201,201
BEGIN DESCRIPTION:
Little Elm Creek 2 9579.32
END DESCRIPTION:
XS GIS Cut Line= 3
      1505458.06      6772071.32      1505547.99      6771493.74
      1505734.74      6770757.09
#Sta/Elev= 30
  4419.5 2222.36  4463.3 2219.92  4497.9 2211.94  4513.9 2206.28  4544.3 2200.28
  4614.7 2196.26  4675.9 2194.14  4847.9 2182.72  4908.6 2181.00  4928.9 2177.24
  4979.5 2172.66  4989.3 2166.65  4989.8 2166.15  5009.4 2166.65  5021.8 2171.77
  5030.6 2173.95  5061.5 2173.90  5090.5 2180.00  5171.0 2182.16  5213.4 2184.28
  5309.1 2184.72  5418.3 2189.63  5459.3 2193.90  5577.1 2215.26  5623.2 2232.41
  5628.9 2237.06  5659.0 2253.50  5700.0 2285.58  5711.5 2291.29  5764.0 2298.57
#Mann=6,-1,0
  4419.5    0.07       0  4614.7    0.16       0  4989.3    0.07       0
  5009.4    0.16       0  5021.8   0.035       0  5171.0    0.16       0
Bank Sta=4989.3,5009.4
Exp/Cntr=0.3,0.1

Type RM Length L Ch R = 1,9378,238,238,238
BEGIN DESCRIPTION:
Little Elm Creek 2 9378.31
END DESCRIPTION:
XS GIS Cut Line= 3
      1505551.44      6772085.22      1505710.55      6771400.35
      1505862.72      6770847.00
#Sta/Elev= 30
  4294.9 2220.99  4378.1 2219.59  4415.2 2208.89  4420.7 2205.64  4425.9 2205.93
  4463.4 2196.11  4497.4 2191.17  4601.5 2184.85  4838.9 2179.05  4887.5 2173.92
  4918.3 2174.23  4955.3 2171.16  4979.9 2171.06  4980.1 2169.31  4980.6 2168.81
  5000.2 2169.31  5010.8 2181.01  5114.5 2182.79  5217.6 2189.28  5290.8 2197.71
  5331.3 2205.89  5363.4 2215.20  5370.9 2221.45  5404.9 2239.38  5410.5 2245.43
  5444.9 2265.70  5456.8 2276.21  5467.1 2281.07  5489.7 2287.80  5571.9 2297.51
#Mann=5,-1,0
  4294.9    0.16       0  4838.9   0.035       0  4955.3    0.16       0
  4980.1    0.07       0  5000.2    0.16       0
Bank Sta=4980.1,5000.2
Exp/Cntr=0.3,0.1

Type RM Length L Ch R = 1,9140,185,185,185
BEGIN DESCRIPTION:
Little Elm Creek 2 9139.511
END DESCRIPTION:
XS GIS Cut Line= 3
      1505655.02      6772037.97      1505916.00      6771488.61
      1505955.00      6770937.99
#Sta/Elev= 30
  4391.8 2219.89  4428.6 2216.68  4474.1 2205.10  4519.5 2188.89  4547.8 2185.19
  4701.3 2182.10  4826.0 2177.34  4884.0 2177.08  4939.6 2177.33  4970.1 2173.93
  4990.6 2171.57  5000.0 2168.86  5000.6 2165.42  5001.1 2164.92  5020.7 2165.42
  5061.2 2179.63  5161.0 2182.78  5261.3 2190.62  5321.4 2199.06  5338.1 2203.17
  5343.1 2202.16  5381.6 2210.41  5401.6 2216.33  5431.7 2229.46  5441.7 2234.72
  5451.7 2242.24  5479.0 2256.50  5484.0 2255.60  5521.9 2282.65  5552.0 2294.52
#Mann=5,-1,0
  4391.8    0.16       0  4884.0   0.035       0  4970.1    0.16       0
  5000.6    0.07       0  5020.7    0.16       0
Bank Sta=5000.6,5020.7
Exp/Cntr=0.3,0.1

Type RM Length L Ch R = 1,8955,226,226,226
BEGIN DESCRIPTION:
Little Elm Creek 2 8954.66
END DESCRIPTION:
XS GIS Cut Line= 3
      1505693.26      6772040.19      1506101.38      6771493.74
      1506042.58      6770954.16
#Sta/Elev= 30
  4313.1 2218.67  4344.1 2216.03  4358.6 2212.73  4373.2 2206.43  4408.7 2196.75
  4423.3 2189.90  4437.9 2187.44  4745.6 2177.03  4794.3 2173.41  4808.9 2175.12
  4829.8 2173.37  4858.9 2174.77  4902.9 2173.08  4965.2 2170.73  4990.8 2164.83
  4991.3 2164.33  5010.9 2164.83  5011.9 2167.50  5031.1 2174.61  5041.1 2180.64
  5103.3 2182.33  5242.3 2190.54  5312.7 2195.92  5377.6 2203.93  5413.3 2213.98
  5443.5 2226.54  5463.6 2238.17  5469.0 2243.60  5533.4 2277.14  5537.9 2277.14
#Mann=5,-1,0
  4313.1    0.16       0  4745.6   0.035       0  4902.9    0.16       0
  4990.8    0.07       0  5010.9    0.16       0
Bank Sta=4990.8,5010.9
Exp/Cntr=0.3,0.1

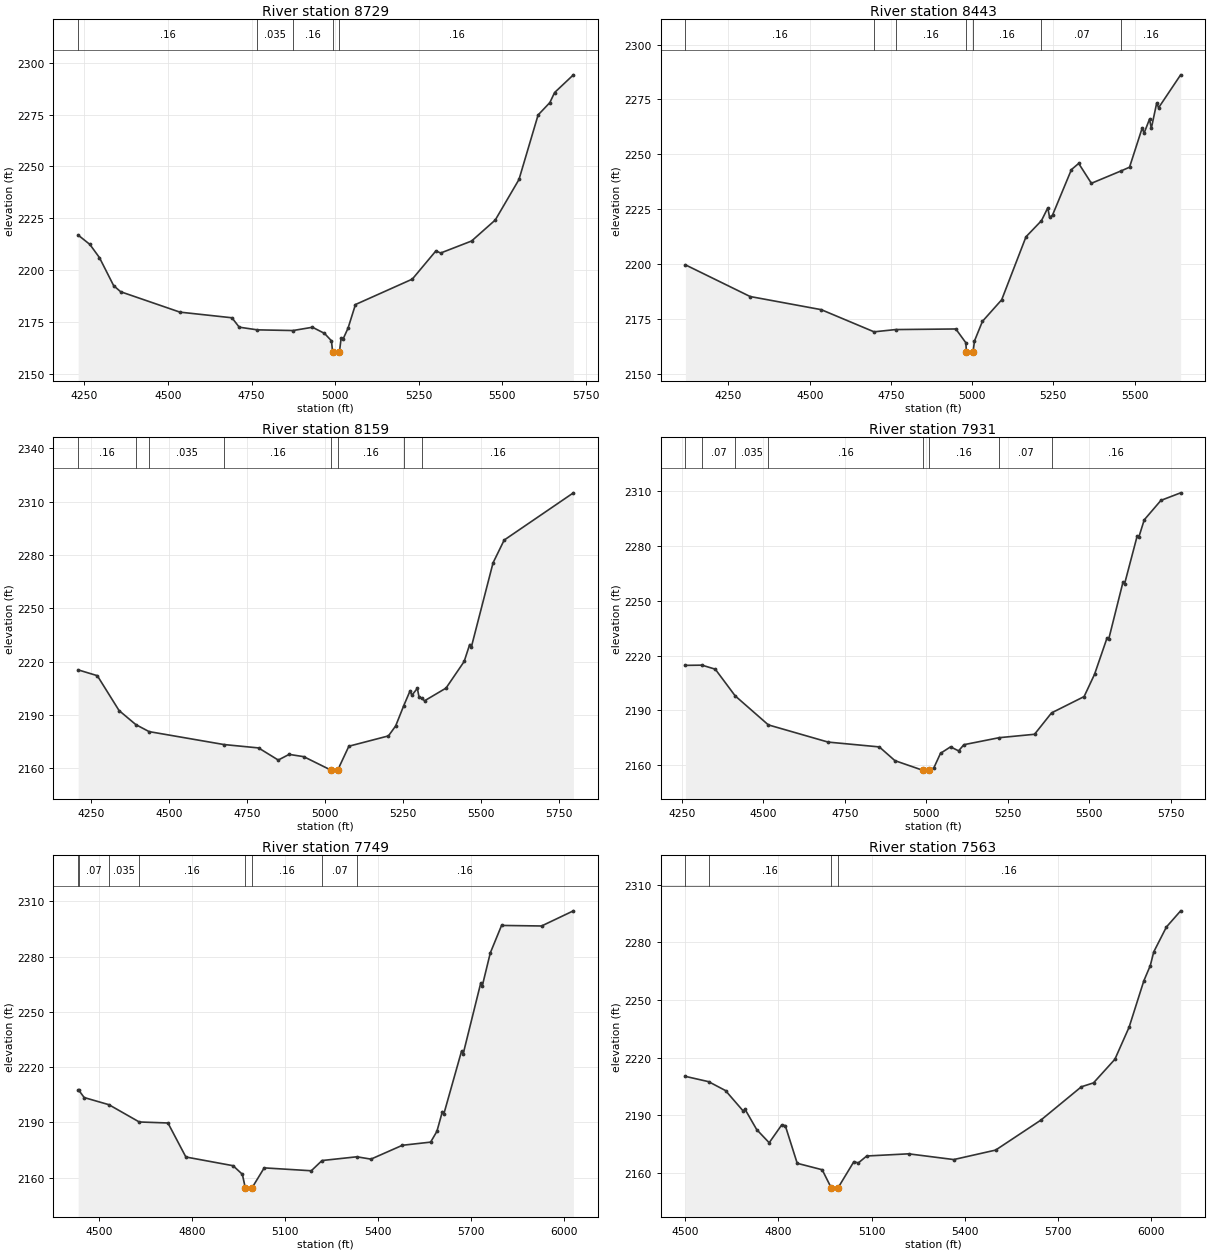
Type RM Length L Ch R = 1,8729,286,286,286
BEGIN DESCRIPTION:
Little Elm Creek 2 8729.38
END DESCRIPTION:
XS GIS Cut Line= 3
      1505731.31      6772054.03      1506308.90      6771542.16
      1506765.44      6770999.14
#Sta/Elev= 30
  4231.3 2216.87  4266.3 2212.37  4294.8 2206.05  4337.4 2192.51  4358.3 2189.57
  4535.6 2179.74  4691.2 2177.02  4713.0 2172.49  4767.2 2171.20  4873.7 2170.87
  4932.1 2172.45  4968.0 2169.50  4988.9 2165.90  4992.3 2160.48  4992.8 2159.98
  5012.6 2160.48  5017.7 2167.04  5024.2 2166.98  5038.5 2172.04  5060.6 2183.40
  5230.6 2195.65  5301.2 2209.25  5315.5 2208.24  5407.9 2214.02  5478.8 2224.15
  5549.7 2243.68  5606.9 2274.78  5642.0 2280.74  5656.3 2285.60  5712.5 2294.13
#Mann=5,-1,0
  4231.3    0.16       0  4767.2   0.035       0  4873.7    0.16       0
  4992.3    0.07       0  5012.6    0.16       0
Bank Sta=4992.3,5012.6
Exp/Cntr=0.3,0.1

Type RM Length L Ch R = 1,8443,284,284,284
BEGIN DESCRIPTION:
Little Elm Creek 2 8442.75
END DESCRIPTION:
XS GIS Cut Line= 3
      1505803.95      6772098.99      1506568.30      6771642.46
      1506851.91      6771075.22
#Sta/Elev= 30
  4117.4 2199.70  4316.6 2185.27  4535.4 2179.29  4698.1 2169.19  4764.4 2170.22
  4949.8 2170.49  4980.6 2164.22  4982.5 2159.99  4983.0 2159.49  5002.8 2159.99
  5007.2 2165.02  5031.7 2173.96  5091.0 2183.79  5165.8 2212.47  5213.4 2219.81
  5232.9 2225.65  5238.5 2221.27  5247.5 2222.36  5305.6 2243.06  5328.0 2245.88
  5367.1 2236.83  5459.6 2242.54  5484.5 2244.16  5523.6 2262.07  5529.2 2259.63
  5546.0 2266.04  5551.6 2261.86  5568.3 2273.49  5573.9 2271.22  5641.9 2286.23
#Mann=7,-1,0
  4117.4    0.16       0  4698.1   0.035       0  4764.4    0.16       0
  4982.5    0.07       0  5002.8    0.16       0  5213.4    0.07       0
  5459.6    0.16       0
Bank Sta=4982.5,5002.8
Exp/Cntr=0.3,0.1

Type RM Length L Ch R = 1,8159,228,228,228
BEGIN DESCRIPTION:
Little Elm Creek 2 8158.54
END DESCRIPTION:
XS GIS Cut Line= 3
      1506575.22      6772576.28      1506782.73      6771801.56
      1507104.38      6771085.63
#Sta/Elev= 30
  4209.6 2215.41  4270.9 2212.15  4340.6 2192.54  4394.4 2184.62  4436.8 2180.69
  4676.8 2173.41  4787.6 2171.51  4850.7 2164.69  4885.5 2167.88  4932.5 2166.59
  5020.4 2158.96  5020.9 2158.46  5041.0 2158.96  5077.0 2172.47  5203.8 2178.27
  5226.9 2183.87  5253.0 2195.35  5273.3 2203.70  5278.8 2201.12  5296.4 2205.04
  5301.9 2200.11  5310.0 2199.54  5319.6 2198.03  5388.3 2205.16  5446.4 2220.13
  5464.1 2229.67  5469.5 2228.30  5539.0 2275.62  5574.6 2288.42  5796.5 2315.00
#Mann=8,-1,0
  4209.6    0.16       0  4394.4    0.07       0  4436.8   0.035       0
  4676.8    0.16       0  5020.4    0.07       0  5041.0    0.16       0
  5253.0    0.07       0  5310.0    0.16       0
Bank Sta=5020.4,5041
Exp/Cntr=0.3,0.1

Type RM Length L Ch R = 1,7931,182,182,182
BEGIN DESCRIPTION:
Little Elm Creek 2 7930.76
END DESCRIPTION:
XS GIS Cut Line= 3
      1506727.41      6772645.43      1506948.75      6771939.90
      1507118.23      6771178.98
#Sta/Elev= 30
  4261.3 2214.64  4312.1 2214.75  4352.9 2212.55  4413.9 2197.98  4515.7 2182.13
  4698.8 2172.75  4856.0 2170.11  4903.9 2162.61  4988.8 2157.39  4989.3 2156.89
  5009.4 2157.39  5023.2 2158.65  5043.7 2166.61  5074.4 2170.14  5099.2 2167.96
  5115.4 2171.32  5223.7 2175.15  5332.1 2177.01  5384.3 2188.69  5484.2 2197.60
  5516.3 2209.81  5554.6 2229.65  5559.8 2229.07  5603.2 2259.93  5608.4 2259.20
  5646.7 2285.10  5651.9 2284.58  5668.6 2294.09  5719.8 2304.71  5780.3 2308.84
#Mann=8,-1,0
  4261.3    0.16       0  4312.1    0.07       0  4413.9   0.035       0
  4515.7    0.16       0  4988.8    0.07       0  5009.4    0.16       0
  5223.7    0.07       0  5384.3    0.16       0
Bank Sta=4988.8,5009.4
Exp/Cntr=0.3,0.1

Type RM Length L Ch R = 1,7749,186,186,186
BEGIN DESCRIPTION:
Little Elm Creek 2 7749.24
END DESCRIPTION:
XS GIS Cut Line= 3
      1507083.64      6772607.43      1507094.01      6772036.75
      1507256.57      6771023.38
#Sta/Elev= 30
  4433.7 2207.63  4434.9 2207.63  4453.1 2203.48  4532.8 2199.60  4630.7 2190.22
  4723.2 2189.67  4781.0 2171.20  4933.2 2166.47  4963.2 2161.80  4972.9 2154.25
  4973.4 2153.75  4993.6 2154.25  5033.6 2165.29  5185.5 2163.72  5220.1 2169.28
  5332.4 2171.31  5377.9 2170.04  5479.2 2177.56  5570.4 2179.28  5590.6 2185.14
  5608.2 2195.85  5613.2 2194.72  5670.1 2228.72  5675.2 2227.15  5732.1 2265.76
  5737.1 2264.26  5762.8 2282.03  5799.1 2296.95  5928.1 2296.65  6030.8 2304.88
#Mann=8,-1,0
  4433.7    0.16       0  4434.9    0.07       0  4532.8   0.035       0
  4630.7    0.16       0  4972.9    0.07       0  4993.6    0.16       0
  5220.1    0.07       0  5332.4    0.16       0
Bank Sta=4972.9,4993.6
Exp/Cntr=0.3,0.1

Type RM Length L Ch R = 1,7563,232,232,232
BEGIN DESCRIPTION:
Little Elm Creek 2 7563.05
END DESCRIPTION:
XS GIS Cut Line= 3
      1507225.44      6772586.66      1507263.49      6772095.54
      1507554.01      6771033.76
#Sta/Elev= 30
  4500.8 2210.17  4575.3 2207.42  4629.8 2202.77  4687.1 2192.04  4692.2 2193.12
  4730.1 2182.43  4770.3 2175.56  4810.4 2184.81  4822.1 2184.48  4860.5 2164.84
  4940.8 2161.48  4970.5 2151.87  4971.0 2151.37  4991.2 2151.87  5042.7 2165.68
  5057.1 2165.03  5084.1 2168.65  5218.9 2169.78  5364.2 2166.79  5498.9 2171.73
  5644.0 2187.31  5774.7 2204.74  5813.8 2206.78  5882.5 2219.07  5928.3 2235.81
  5975.8 2260.03  5996.5 2267.95  6007.6 2275.09  6048.3 2288.06  6094.2 2296.51
#Mann=4,-1,0
  4500.8   0.035       0  4575.3    0.16       0  4970.5    0.07       0
  4991.2    0.16       0
Bank Sta=4970.5,4991.2
Exp/Cntr=0.3,0.1