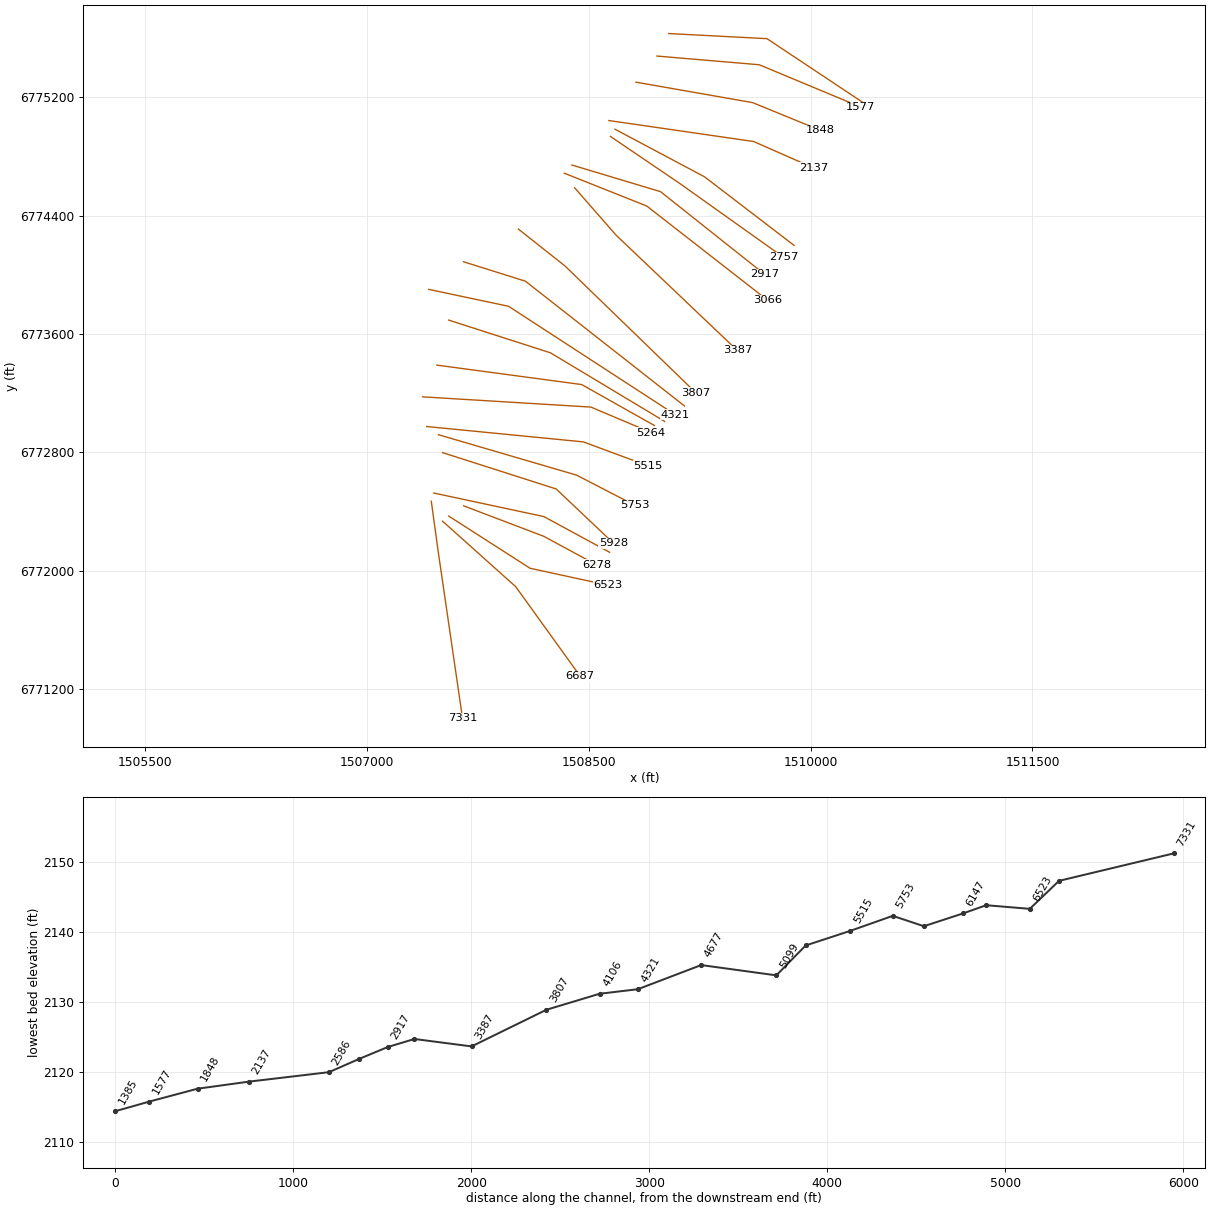
HEC-RAS study Little Elm Creek 2.prj: Little Elm Creek 2 Base Level Engineering

--- Little Elm Creek 2.g01 (geometry) --- (continued)

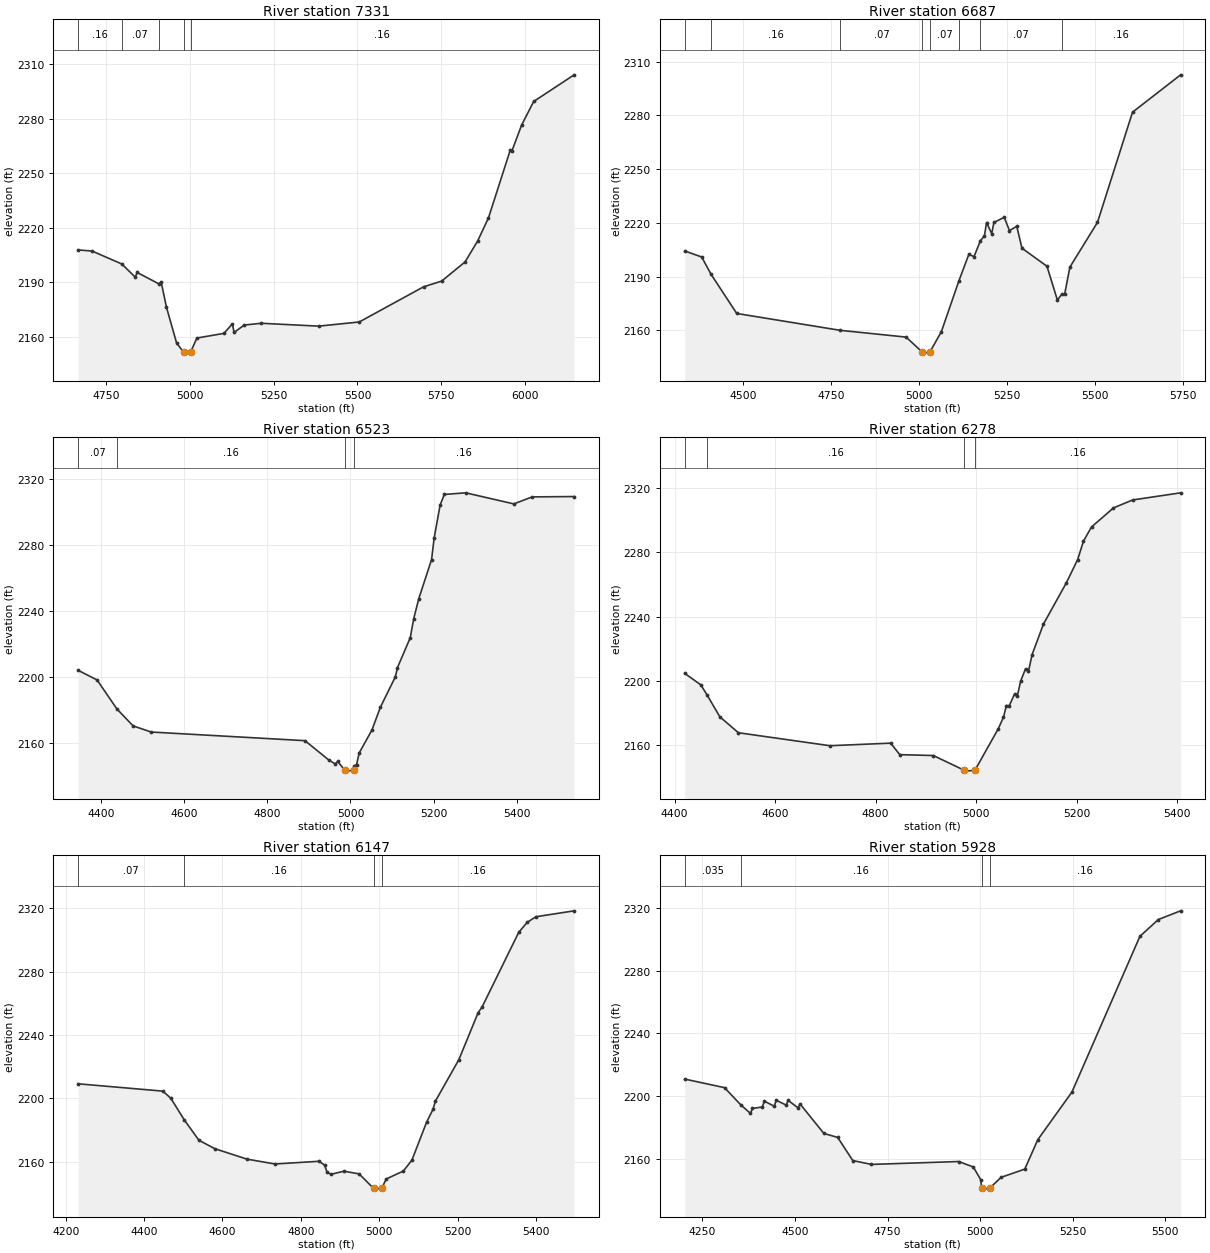
Type RM Length L Ch R = 1,7331,644,644,644
BEGIN DESCRIPTION:
Little Elm Creek 2 7330.92
END DESCRIPTION:
XS GIS Cut Line= 3
      1507436.42      6772469.08      1507481.38      6772140.51
      1507647.37      6771002.79
#Sta/Elev= 30
  4665.8 2207.87  4707.3 2207.24  4795.6 2200.18  4836.6 2192.88  4841.6 2195.52
  4906.1 2189.29  4913.8 2190.06  4929.3 2176.48  4959.6 2156.80  4980.7 2151.70
  4981.2 2151.20  5001.4 2151.70  5020.2 2159.48  5101.0 2162.04  5126.3 2167.25
  5131.4 2162.55  5161.7 2166.61  5212.2 2167.59  5384.0 2166.02  5505.3 2168.30
  5697.3 2187.60  5751.3 2190.75  5821.3 2201.26  5859.0 2212.79  5891.3 2225.46
  5956.3 2262.65  5961.3 2262.19  5990.3 2276.43  6026.3 2289.37  6147.2 2304.00
#Mann=5,-1,0
  4665.8    0.16       0  4795.6    0.07       0  4906.1    0.16       0
  4980.7    0.07       0  5001.4    0.16       0
Bank Sta=4980.7,5001.4
Exp/Cntr=0.3,0.1

Type RM Length L Ch R = 1,6687,164,164,164
BEGIN DESCRIPTION:
Little Elm Creek 2 6686.64
END DESCRIPTION:
XS GIS Cut Line= 3
      1507512.53      6772334.18      1508007.10      6771891.48
      1508442.90      6771286.21
#Sta/Elev= 30
  4335.0 2204.31  4383.5 2200.92  4410.0 2191.26  4483.0 2169.41  4777.1 2160.00
  4964.4 2156.22  5010.7 2147.78  5011.2 2147.28  5031.7 2147.78  5064.7 2159.32
  5114.2 2187.49  5142.7 2202.43  5157.4 2201.12  5175.7 2210.07  5186.9 2212.68
  5193.0 2220.14  5207.7 2213.97  5213.9 2220.19  5243.3 2223.09  5258.1 2215.65
  5278.9 2218.06  5293.6 2205.86  5364.8 2195.74  5394.3 2176.91  5406.5 2180.03
  5415.2 2180.39  5429.9 2195.29  5508.3 2220.25  5607.9 2281.73  5744.6 2302.59
#Mann=8,-1,0
  4335.0    0.07       0  4410.0    0.16       0  4777.1    0.07       0
  5010.7    0.07       0  5031.7    0.07       0  5114.2    0.16       0
  5175.7    0.07       0  5406.5    0.16       0
Bank Sta=5010.7,5031.7
Exp/Cntr=0.3,0.1

Type RM Length L Ch R = 1,6523,245,245,245
BEGIN DESCRIPTION:
Little Elm Creek 2 6523.4
END DESCRIPTION:
XS GIS Cut Line= 3
      1507553.98      6772368.80      1508103.94      6772015.99
      1508629.70      6771901.85
#Sta/Elev= 30
  4345.9 2204.14  4391.2 2198.34  4439.1 2180.76  4477.8 2170.60  4521.4 2166.89
  4890.7 2161.68  4948.2 2149.92  4963.4 2147.64  4969.3 2149.11  4986.5 2143.78
  4987.0 2143.28  5007.5 2143.78  5009.5 2146.47  5014.6 2147.25  5020.8 2154.20
  5051.5 2168.12  5072.0 2181.97  5107.8 2200.26  5112.9 2205.83  5143.6 2223.87
  5151.8 2235.25  5164.1 2247.47  5194.8 2271.08  5200.9 2283.94  5215.3 2303.99
  5225.5 2310.40  5276.7 2311.37  5392.4 2304.69  5436.5 2308.91  5537.3 2309.12
#Mann=4,-1,0
  4345.9    0.07       0  4439.1    0.16       0  4986.5    0.07       0
  5007.5    0.16       0
Bank Sta=4986.5,5007.5
Exp/Cntr=0.3,0.1

Type RM Length L Ch R = 1,6278,131,131,131
BEGIN DESCRIPTION:
Little Elm Creek 2 6278.169
END DESCRIPTION:
XS GIS Cut Line= 3
      1507654.97      6772438.01      1508196.91      6772231.92
      1508554.97      6772038.02
#Sta/Elev= 30
  4420.2 2204.68  4452.3 2197.49  4464.2 2191.48  4490.2 2177.60  4527.2 2167.69
  4709.1 2159.62  4830.2 2161.22  4848.2 2154.06  4915.1 2153.51  4976.8 2144.30
  4977.3 2143.80  4997.8 2144.30  5044.4 2170.23  5054.7 2177.41  5060.6 2184.63
  5066.2 2184.54  5076.7 2191.77  5082.4 2190.74  5088.8 2199.80  5098.6 2207.57
  5104.3 2205.83  5111.6 2216.30  5134.3 2235.37  5179.8 2261.00  5202.3 2275.49
  5213.9 2286.99  5229.9 2295.78  5273.6 2307.63  5311.7 2312.58  5407.2 2317.02
#Mann=4,-1,0
  4420.2    0.07       0  4464.2    0.16       0  4976.8    0.07       0
  4997.8    0.16       0
Bank Sta=4976.8,4997.8
Exp/Cntr=0.3,0.1

Type RM Length L Ch R = 1,6147,219,219,219
BEGIN DESCRIPTION:
Little Elm Creek 2 6147.13
END DESCRIPTION:
XS GIS Cut Line= 3
      1507453.69      6772524.42      1508197.33      6772365.32
      1508641.75      6772124.16
#Sta/Elev= 30
  4231.7 2209.11  4447.8 2204.49  4468.2 2199.95  4501.8 2186.57  4539.8 2173.48
  4580.7 2168.13  4662.5 2161.56  4734.1 2158.49  4846.6 2160.20  4860.9 2157.75
  4867.1 2153.14  4877.3 2152.02  4910.4 2153.93  4948.9 2152.24  4985.6 2143.12
  4986.1 2142.62  5006.6 2143.12  5018.0 2149.04  5061.7 2154.04  5083.6 2160.92
  5121.6 2185.19  5137.4 2192.94  5143.5 2198.14  5203.4 2224.33  5252.8 2254.08
  5262.6 2257.52  5356.4 2304.79  5378.2 2311.10  5400.1 2314.58  5497.8 2318.32
#Mann=4,-1,0
  4231.7    0.07       0  4501.8    0.16       0  4985.6    0.07       0
  5006.6    0.16       0
Bank Sta=4985.6,5006.6
Exp/Cntr=0.3,0.1

Type RM Length L Ch R = 1,5928,175,175,175
BEGIN DESCRIPTION:
Little Elm Creek 2 5928.09
END DESCRIPTION:
XS GIS Cut Line= 3
      1507512.47      6772797.67      1508280.34      6772552.09
      1508667.68      6772185.49
#Sta/Elev= 30
  4202.0 2210.89  4309.6 2205.43  4353.3 2194.53  4379.7 2189.02  4384.9 2192.17
  4411.8 2193.11  4417.1 2196.86  4444.0 2193.57  4449.2 2197.41  4476.2 2194.31
  4481.4 2197.36  4508.3 2192.52  4513.6 2195.07  4577.9 2176.27  4615.3 2173.72
  4656.1 2158.98  4706.5 2156.54  4942.2 2158.38  4981.6 2154.90  5001.3 2146.92
  5004.3 2141.30  5004.8 2140.80  5025.3 2141.30  5056.6 2148.31  5120.6 2153.54
  5155.8 2172.30  5248.0 2202.63  5431.6 2301.81  5481.4 2312.50  5541.5 2318.03
#Mann=4,-1,0
  4202.0   0.035       0  4353.3    0.16       0  5004.3    0.07       0
  5025.3    0.16       0
Bank Sta=5004.3,5025.3
Exp/Cntr=0.3,0.1

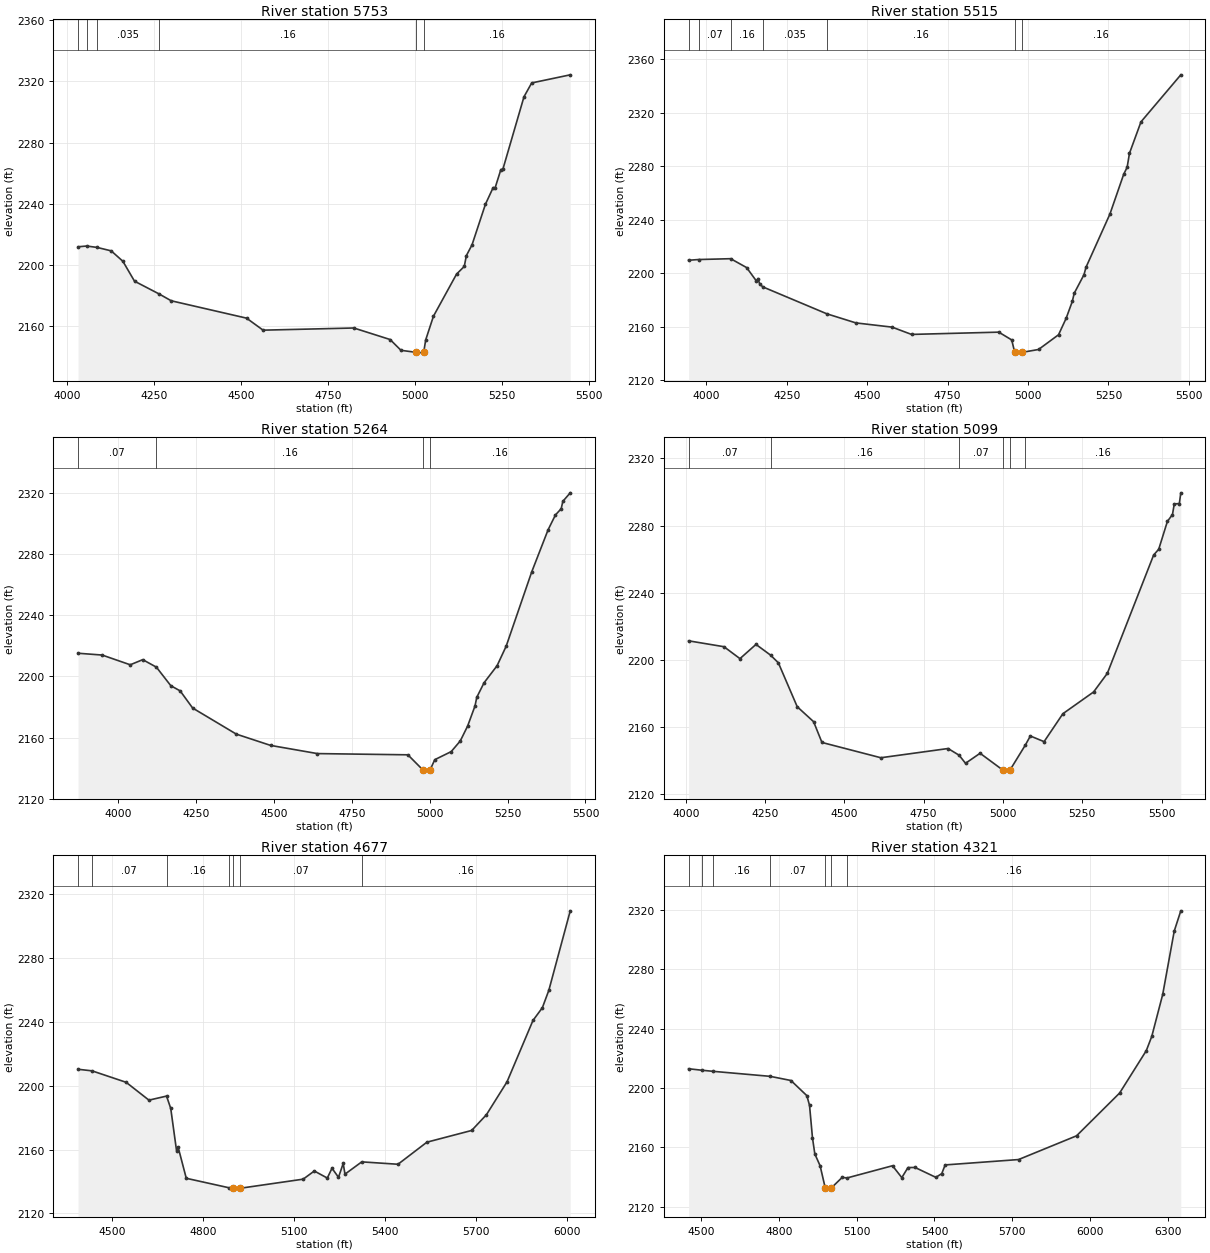
Type RM Length L Ch R = 1,5753,238,238,238
BEGIN DESCRIPTION:
Little Elm Creek 2 5753.39
END DESCRIPTION:
XS GIS Cut Line= 3
      1507484.87      6772918.70      1508418.68      6772645.47
      1508809.93      6772442.99
#Sta/Elev= 30
  4031.8 2211.84  4056.5 2212.34  4086.2 2211.45  4127.1 2209.18  4160.6 2202.37
  4194.0 2189.35  4264.3 2181.03  4299.5 2176.52  4515.7 2165.17  4563.3 2157.30
  4823.8 2158.72  4928.0 2151.18  4959.2 2144.12  5003.3 2142.78  5003.8 2142.28
  5024.4 2142.78  5030.3 2151.00  5052.5 2166.44  5118.9 2194.00  5141.0 2199.00
  5147.0 2206.07  5163.2 2213.09  5201.8 2239.70  5223.9 2250.57  5229.6 2250.43
  5246.1 2262.38  5251.7 2262.47  5312.5 2310.00  5334.6 2319.03  5445.3 2324.34
#Mann=6,-1,0
  4031.8    0.07       0  4056.5    0.16       0  4086.2   0.035       0
  4264.3    0.16       0  5003.3    0.07       0  5024.4    0.16       0
Bank Sta=5003.3,5024.4
Exp/Cntr=0.3,0.1

Type RM Length L Ch R = 1,5515,251,251,251
BEGIN DESCRIPTION:
Little Elm Creek 2 5514.62
END DESCRIPTION:
XS GIS Cut Line= 3
      1507405.32      6772974.04      1508463.65      6772870.29
      1508901.43      6772708.27
#Sta/Elev= 30
  3944.8 2209.59  3975.8 2210.13  4075.6 2210.76  4125.3 2204.10  4155.5 2194.10
  4160.5 2195.92  4165.5 2192.05  4175.3 2189.70  4374.7 2169.53  4464.9 2162.74
  4577.5 2159.58  4637.8 2154.13  4909.1 2155.83  4949.3 2150.01  4958.8 2140.64
  4959.3 2140.14  4979.9 2140.64  5032.7 2142.86  5094.9 2153.88  5118.6 2166.21
  5137.6 2178.75  5143.7 2184.95  5174.1 2198.82  5180.2 2204.30  5254.6 2244.11
  5297.5 2273.91  5308.2 2279.16  5315.4 2289.57  5351.2 2313.10  5475.0 2348.26
#Mann=7,-1,0
  3944.8    0.16       0  3975.8    0.07       0  4075.6    0.16       0
  4175.3   0.035       0  4374.7    0.16       0  4958.8    0.07       0
  4979.9    0.16       0
Bank Sta=4958.8,4979.9
Exp/Cntr=0.3,0.1

Type RM Length L Ch R = 1,5264,165,165,165
BEGIN DESCRIPTION:
Little Elm Creek 2 5263.98
END DESCRIPTION:
XS GIS Cut Line= 3
      1507377.61      6773174.65      1508515.53      6773105.48
      1508921.28      6772933.54
#Sta/Elev= 30
  3870.3 2215.07  3947.8 2213.89  4038.0 2207.53  4078.1 2210.88  4122.0 2205.98
  4168.2 2193.88  4198.3 2190.47  4238.4 2179.27  4378.6 2162.23  4488.8 2154.85
  4639.1 2149.51  4929.6 2148.71  4979.2 2138.55  4979.7 2138.05  5000.3 2138.55
  5015.9 2145.53  5068.7 2150.80  5097.8 2157.75  5121.5 2167.51  5145.2 2180.66
  5150.9 2186.30  5174.3 2195.80  5216.1 2206.93  5245.3 2219.70  5327.2 2268.17
  5380.0 2295.79  5403.6 2305.47  5421.9 2309.47  5427.3 2314.33  5451.0 2319.88
#Mann=4,-1,0
  3870.3    0.07       0  4122.0    0.16       0  4979.2    0.07       0
  5000.3    0.16       0
Bank Sta=4979.2,5000.3
Exp/Cntr=0.3,0.1

Type RM Length L Ch R = 1,5099,422,422,422
BEGIN DESCRIPTION:
Little Elm Creek 2 5098.83
END DESCRIPTION:
XS GIS Cut Line= 3
      1507474.50      6773389.08      1508453.27      6773257.66
      1508944.43      6772980.95
#Sta/Elev= 30
  4009.1 2211.36  4120.6 2207.85  4171.0 2200.75  4221.5 2209.22  4267.4 2202.85
  4292.1 2198.23  4351.5 2172.11  4403.1 2163.21  4429.4 2150.85  4615.0 2141.75
  4826.9 2147.24  4861.7 2143.25  4881.9 2138.44  4927.8 2144.41  5000.5 2134.28
  5001.0 2133.78  5021.6 2134.28  5070.7 2149.38  5086.2 2154.70  5129.5 2151.33
  5188.8 2167.97  5285.6 2180.92  5328.9 2192.02  5474.8 2262.45  5490.8 2265.88
  5518.2 2282.50  5534.1 2286.51  5539.8 2292.82  5555.8 2293.11  5560.4 2299.47
#Mann=6,-1,0
  4009.1    0.07       0  4267.4    0.16       0  4861.7    0.07       0
  5000.5    0.07       0  5021.6    0.07       0  5070.7    0.16       0
Bank Sta=5000.5,5021.6
Exp/Cntr=0.3,0.1

Type RM Length L Ch R = 1,4677,356,356,356
BEGIN DESCRIPTION:
Little Elm Creek 2 4676.92
END DESCRIPTION:
XS GIS Cut Line= 3
      1507553.97      6773693.46      1508242.29      6773472.09
      1509013.61      6773008.61
#Sta/Elev= 30
  4386.7 2210.25  4432.9 2209.26  4545.3 2202.10  4620.5 2190.93  4678.6 2193.47
  4692.4 2185.73  4711.5 2159.36  4716.8 2161.50  4743.6 2142.03  4885.0 2136.08
  4898.7 2135.75  4899.2 2135.25  4919.8 2135.75  5128.9 2141.48  5165.8 2146.59
  5208.6 2142.18  5224.1 2148.31  5245.5 2142.65  5261.0 2151.30  5266.9 2144.62
  5322.2 2152.31  5441.7 2150.81  5536.9 2164.62  5684.6 2171.96  5733.2 2181.79
  5801.2 2202.40  5886.7 2240.78  5917.7 2248.77  5939.1 2259.71  6009.6 2309.39
#Mann=7,-1,0
  4386.7    0.16       0  4432.9    0.07       0  4678.6    0.16       0
  4885.0    0.07       0  4898.7    0.07       0  4919.8    0.07       0
  5322.2    0.16       0
Bank Sta=4898.7,4919.8
Exp/Cntr=0.3,0.1

Type RM Length L Ch R = 1,4321,215,215,215
BEGIN DESCRIPTION:
Little Elm Creek 2 4321.31
END DESCRIPTION:
XS GIS Cut Line= 3
      1507419.13      6773900.97      1507958.68      6773786.83
      1509086.24      6773053.58
#Sta/Elev= 30
  4452.6 2212.93  4504.4 2211.92  4544.9 2211.23  4767.1 2207.81  4847.0 2205.01
  4908.3 2194.79  4918.6 2188.23  4929.9 2166.43  4939.0 2155.51  4959.4 2147.52
  4979.5 2132.30  4980.0 2131.80  5000.7 2132.30  5044.6 2139.74  5062.8 2139.32
  5238.3 2147.56  5274.1 2139.56  5297.9 2146.35  5325.3 2146.39  5405.3 2139.74
  5428.1 2142.27  5441.1 2148.11  5723.9 2151.73  5947.3 2167.72  6113.4 2196.57
  6216.1 2225.12  6237.2 2234.71  6279.4 2263.04  6323.8 2305.73  6349.1 2319.37
#Mann=7,-1,0
  4452.6    0.16       0  4504.4    0.07       0  4544.9    0.16       0
  4767.1    0.07       0  4979.5    0.07       0  5000.7    0.07       0
  5062.8    0.16       0
Bank Sta=4979.5,5000.7
Exp/Cntr=0.3,0.1

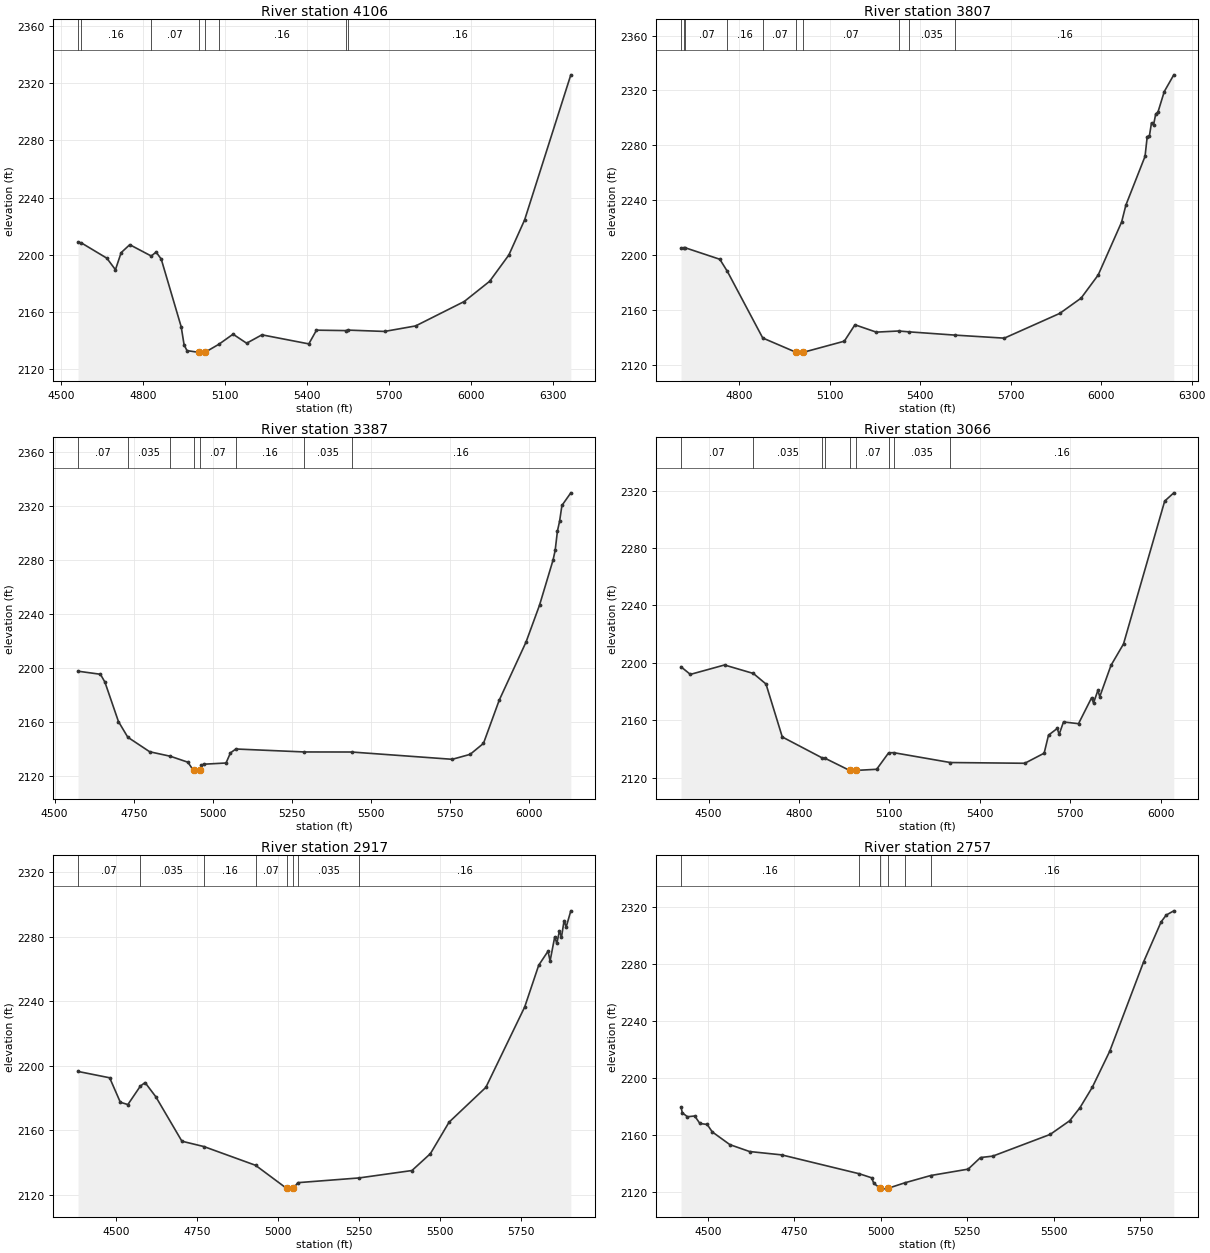
Type RM Length L Ch R = 1,4106,299,299,299
BEGIN DESCRIPTION:
Little Elm Creek 2 4106.49
END DESCRIPTION:
XS GIS Cut Line= 3
      1507654.32      6774087.74      1508072.82      6773956.31
      1509148.11      6773112.67
#Sta/Elev= 30
  4561.5 2208.65  4572.8 2208.40  4667.0 2197.60  4698.5 2189.53  4719.4 2201.48
  4750.9 2207.05  4829.7 2199.12  4847.4 2201.89  4866.2 2197.01  4939.4 2149.58
  4950.0 2136.96  4960.5 2132.93  5004.9 2131.65  5005.4 2131.15  5026.1 2131.65
  5077.7 2137.39  5129.4 2144.41  5179.1 2138.09  5235.2 2143.96  5406.9 2137.62
  5435.1 2147.23  5542.1 2146.92  5551.6 2147.26  5684.4 2146.33  5798.3 2150.19
  5976.4 2167.28  6069.5 2181.44  6140.0 2199.89  6197.7 2224.43  6366.9 2325.95
#Mann=8,-1,0
  4561.5    0.07       0  4572.8    0.16       0  4829.7    0.07       0
  5004.9    0.07       0  5026.1    0.07       0  5077.7    0.16       0
  5542.1   0.035       0  5551.6    0.16       0
Bank Sta=5004.9,5026.1
Exp/Cntr=0.3,0.1

Type RM Length L Ch R = 1,3807,420,420,420
BEGIN DESCRIPTION:
Little Elm Creek 2 3806.76
END DESCRIPTION:
XS GIS Cut Line= 3
      1508024.43      6774309.07      1508339.13      6774060.07
      1509224.22      6773202.64
#Sta/Elev= 30
  4607.2 2205.45  4615.7 2205.60  4621.4 2205.51  4735.8 2197.16  4761.0 2188.27
  4878.1 2139.87  4989.7 2129.36  4990.2 2128.86  5010.9 2129.36  5148.5 2137.55
  5183.7 2149.49  5254.5 2144.14  5328.5 2144.97  5364.3 2144.33  5516.0 2141.96
  5678.9 2139.76  5862.8 2157.78  5933.5 2168.90  5990.1 2185.70  6067.8 2224.25
  6082.0 2236.62  6145.5 2272.09  6152.7 2286.47  6159.7 2286.65  6166.9 2296.48
  6173.8 2295.06  6181.0 2303.05  6188.0 2304.07  6209.3 2319.25  6240.8 2331.39
#Mann=10,-1,0
  4607.2    0.07       0  4615.7    0.16       0  4621.4    0.07       0
  4761.0    0.16       0  4878.1    0.07       0  4989.7    0.07       0
  5010.9    0.07       0  5328.5    0.16       0  5364.3   0.035       0
  5516.0    0.16       0
Bank Sta=4989.7,5010.9
Exp/Cntr=0.3,0.1

Type RM Length L Ch R = 1,3387,321,321,321
BEGIN DESCRIPTION:
Little Elm Creek 2 3386.799
END DESCRIPTION:
XS GIS Cut Line= 3
      1508405.01      6774587.99      1508685.38      6774267.53
      1509504.98      6773488.02
#Sta/Elev= 30
  4574.2 2197.59  4644.9 2195.32  4659.1 2189.50  4701.8 2160.34  4731.4 2148.72
  4800.6 2137.96  4866.1 2134.62  4921.1 2130.24  4939.0 2124.13  4939.5 2123.63
  4960.2 2124.13  4963.8 2128.11  4971.4 2128.75  5041.7 2129.65  5055.8 2137.15
  5072.7 2140.01  5289.3 2137.82  5438.4 2137.78  5756.4 2132.38  5813.0 2136.05
  5855.1 2144.16  5904.8 2176.10  5989.7 2219.22  6032.2 2246.45  6074.7 2279.63
  6081.6 2286.93  6088.8 2301.33  6095.7 2308.67  6103.0 2320.26  6131.1 2329.61
#Mann=8,-1,0
  4574.2    0.07       0  4731.4   0.035       0  4866.1    0.07       0
  4939.0    0.07       0  4960.2    0.07       0  5072.7    0.16       0
  5289.3   0.035       0  5438.4    0.16       0
Bank Sta=4939,4960.2
Exp/Cntr=0.3,0.1

Type RM Length L Ch R = 1,3066,149,149,149
BEGIN DESCRIPTION:
Little Elm Creek 2 3065.55
END DESCRIPTION:
XS GIS Cut Line= 3
      1508335.63      6774686.11      1508892.52      6774464.73
      1509708.77      6773828.33
#Sta/Elev= 30
  4408.9 2197.29  4439.8 2192.02  4553.1 2198.57  4648.8 2192.67  4690.7 2185.32
  4744.7 2148.47  4876.0 2134.01  4885.3 2133.78  4968.0 2125.19  4968.5 2124.69
  4989.2 2125.19  5057.7 2125.97  5097.4 2137.43  5113.9 2137.55  5302.2 2130.67
  5549.0 2130.16  5613.2 2137.18  5627.7 2149.75  5656.6 2154.38  5662.9 2150.29
  5677.4 2158.92  5727.2 2157.72  5770.6 2175.77  5776.9 2172.08  5791.4 2180.88
  5797.7 2176.53  5834.8 2198.27  5876.4 2213.21  6013.0 2312.65  6043.2 2318.40
#Mann=9,-1,0
  4408.9    0.07       0  4648.8   0.035       0  4876.0    0.16       0
  4885.3    0.07       0  4968.0    0.07       0  4989.2    0.07       0
  5097.4    0.16       0  5113.9   0.035       0  5302.2    0.16       0
Bank Sta=4968,4989.2
Exp/Cntr=0.3,0.1

Type RM Length L Ch R = 1,2917,160,160,160
BEGIN DESCRIPTION:
Little Elm Creek 2 2916.93
END DESCRIPTION:
XS GIS Cut Line= 3
      1508387.51      6774741.44      1508985.91      6774561.58
      1509689.66      6774002.72
#Sta/Elev= 30
  4382.0 2196.43  4479.7 2192.51  4512.7 2177.36  4536.0 2175.93  4574.6 2187.35
  4589.2 2189.55  4622.3 2180.79  4703.1 2153.23  4771.1 2149.91  4930.8 2138.31
  5026.6 2124.05  5027.1 2123.55  5047.8 2124.05  5061.5 2127.55  5250.9 2130.48
  5414.3 2135.07  5471.3 2145.50  5529.0 2165.01  5642.8 2186.57  5762.9 2236.38
  5806.2 2262.21  5835.0 2270.92  5841.4 2264.87  5855.8 2279.85  5862.2 2275.71
  5870.3 2283.46  5876.6 2279.61  5884.7 2289.83  5891.1 2285.88  5905.5 2295.92
#Mann=8,-1,0
  4382.0    0.07       0  4574.6   0.035       0  4771.1    0.16       0
  4930.8    0.07       0  5026.6    0.07       0  5047.8    0.07       0
  5061.5   0.035       0  5250.9    0.16       0
Bank Sta=5026.6,5047.8
Exp/Cntr=0.3,0.1

Type RM Length L Ch R = 1,2757,171,171,171
BEGIN DESCRIPTION:
Little Elm Creek 2 2756.7
END DESCRIPTION:
XS GIS Cut Line= 3
      1508646.98      6774935.10      1509120.79      6774613.46
      1509815.95      6774118.89
#Sta/Elev= 30
  4421.8 2179.52  4425.5 2175.51  4440.4 2172.76  4461.4 2173.28  4476.4 2168.01
  4497.4 2167.34  4512.3 2162.07  4563.2 2153.13  4620.1 2148.30  4713.0 2145.94
  4937.7 2132.66  4973.4 2129.82  4979.5 2125.97  4998.5 2122.36  4999.0 2121.86
  5019.8 2122.36  5069.2 2126.29  5144.5 2131.44  5252.6 2135.92  5288.3 2144.07
  5323.9 2145.07  5490.0 2160.34  5546.5 2169.98  5576.0 2179.09  5611.7 2193.44
  5662.1 2218.75  5760.5 2281.80  5810.9 2309.78  5825.6 2314.54  5847.6 2317.54
#Mann=6,-1,0
  4421.8    0.16       0  4937.7   0.035       0  4998.5   0.035       0
  5019.8   0.035       0  5069.2    0.07       0  5144.5    0.16       0
Bank Sta=4998.5,5019.8
Exp/Cntr=0.3,0.1

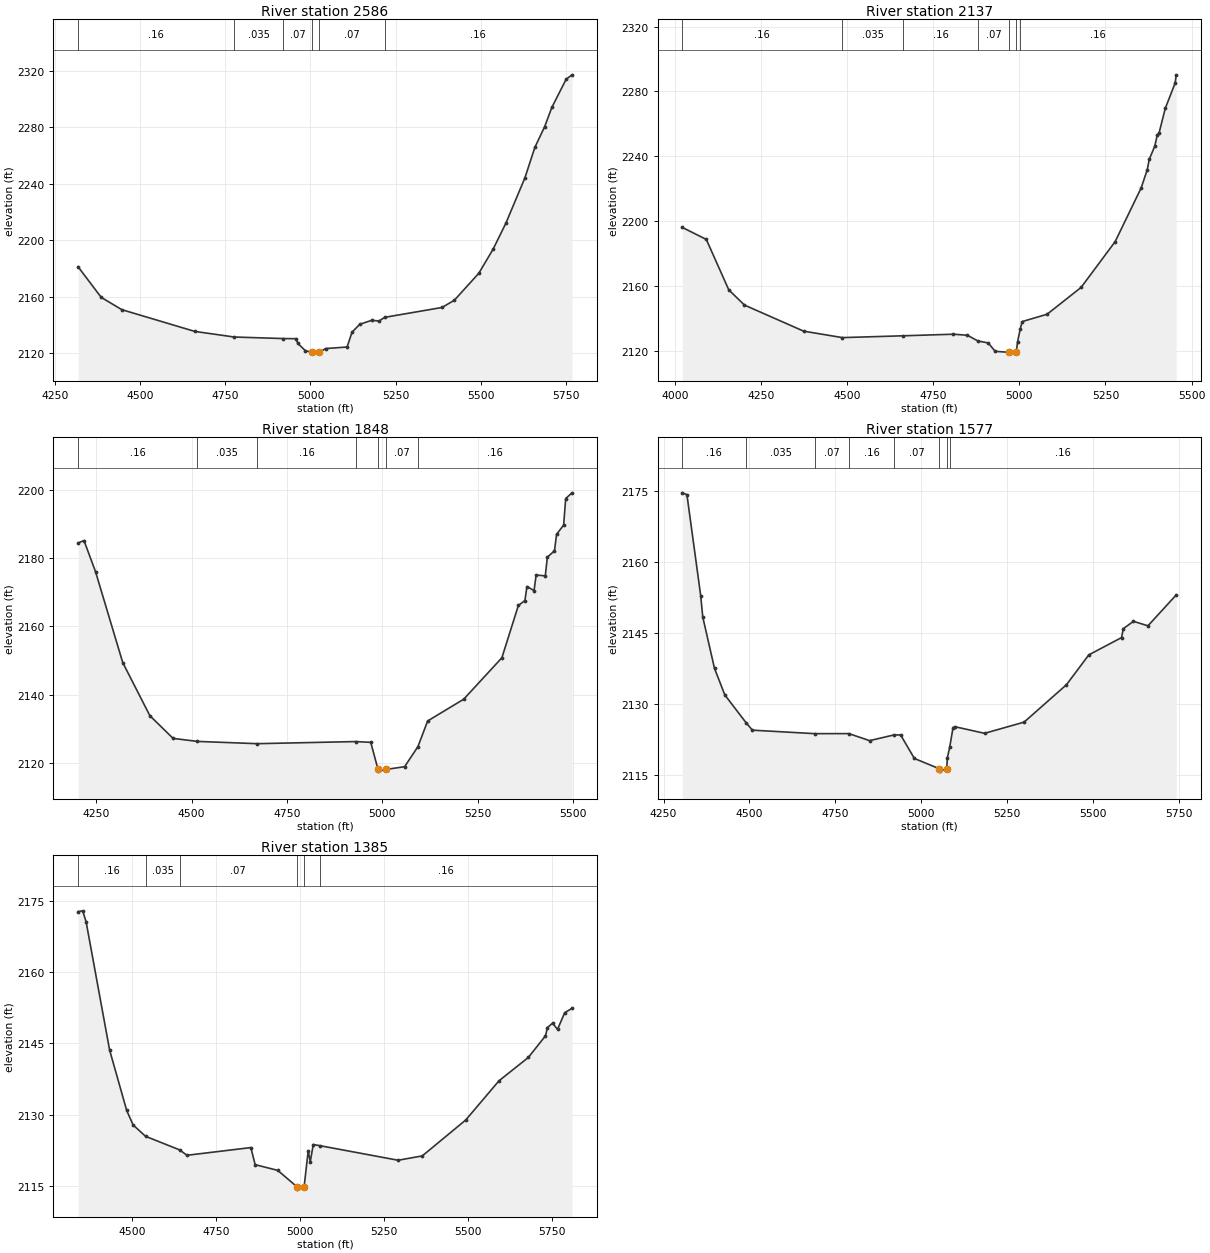
Type RM Length L Ch R = 1,2586,449,449,449
BEGIN DESCRIPTION:
Little Elm Creek 2 2585.66
END DESCRIPTION:
XS GIS Cut Line= 3
      1508678.05      6774983.55      1509283.35      6774661.88
      1509888.62      6774198.41
#Sta/Elev= 30
  4318.8 2181.15  4386.4 2159.51  4446.7 2150.78  4660.8 2135.35  4776.5 2131.37
  4919.6 2130.28  4957.2 2130.18  4962.9 2126.81  4984.9 2121.71  5005.1 2120.45
  5005.6 2119.95  5026.4 2120.45  5044.1 2123.19  5107.3 2124.28  5121.8 2134.80
  5144.5 2140.41  5179.9 2143.24  5200.7 2142.68  5217.5 2145.32  5385.6 2152.32
  5422.0 2157.50  5493.6 2176.63  5535.3 2193.64  5572.5 2211.91  5628.6 2244.23
  5657.7 2265.78  5686.5 2280.52  5707.5 2294.14  5749.4 2314.11  5766.6 2317.25
#Mann=6,-1,0
  4318.8    0.16       0  4776.5   0.035       0  4919.6    0.07       0
  5005.1    0.07       0  5026.4    0.07       0  5217.5    0.16       0
Bank Sta=5005.1,5026.4
Exp/Cntr=0.3,0.1

Type RM Length L Ch R = 1,2137,289,289,289
BEGIN DESCRIPTION:
Little Elm Creek 2 2137.02
END DESCRIPTION:
XS GIS Cut Line= 3
      1508636.58      6775042.33      1509615.38      6774900.53
      1510021.75      6774721.45
#Sta/Elev= 30
  4022.1 2196.13  4091.7 2188.73  4156.9 2157.62  4202.4 2148.24  4374.2 2132.15
  4486.6 2128.17  4662.3 2129.29  4808.6 2130.26  4849.1 2129.64  4879.7 2126.11
  4909.7 2124.89  4929.9 2119.71  4969.8 2119.10  4970.3 2118.60  4991.1 2119.10
  4994.7 2125.36  5002.7 2133.53  5008.4 2138.06  5080.6 2142.59  5179.3 2159.15
  5278.1 2187.39  5353.5 2220.49  5371.3 2231.80  5376.9 2238.07  5393.2 2246.38
  5400.2 2253.16  5405.7 2254.58  5423.5 2269.56  5452.3 2285.32  5455.2 2290.25
#Mann=7,-1,0
  4022.1    0.16       0  4486.6   0.035       0  4662.3    0.16       0
  4879.7    0.07       0  4969.8    0.07       0  4991.1    0.07       0
  5002.7    0.16       0
Bank Sta=4969.8,4991.1
Exp/Cntr=0.3,0.1

Type RM Length L Ch R = 1,1848,271,271,271
BEGIN DESCRIPTION:
Little Elm Creek 2 1847.83
END DESCRIPTION:
XS GIS Cut Line= 3
      1508819.87      6775301.73      1509608.47      6775163.38
      1510065.00      6774976.62
#Sta/Elev= 30
  4202.9 2184.43  4218.3 2185.14  4248.5 2176.03  4319.8 2149.40  4390.9 2133.82
  4451.8 2127.18  4515.0 2126.30  4672.2 2125.63  4930.3 2126.25  4969.6 2126.02
  4988.6 2118.09  4989.1 2117.59  5009.9 2118.09  5058.3 2118.89  5093.2 2124.77
  5118.6 2132.28  5213.2 2138.67  5313.1 2150.80  5356.3 2166.12  5373.4 2167.57
  5378.8 2171.67  5397.4 2170.49  5402.8 2175.03  5426.8 2174.80  5432.3 2180.28
  5450.9 2182.13  5456.3 2186.94  5474.9 2189.68  5480.3 2197.45  5496.8 2199.12
#Mann=7,-1,0
  4202.9    0.16       0  4515.0   0.035       0  4672.2    0.16       0
  4930.3    0.07       0  4988.6    0.07       0  5009.9    0.07       0
  5093.2    0.16       0
Bank Sta=4988.6,5009.9
Exp/Cntr=0.3,0.1

Type RM Length L Ch R = 1,1577,192,192,192
BEGIN DESCRIPTION:
Little Elm Creek 2 1577.33
END DESCRIPTION:
XS GIS Cut Line= 3
      1508961.68      6775478.12      1509653.43      6775419.33
      1510339.97      6775132.98
#Sta/Elev= 30
  4304.8 2174.64  4318.2 2174.26  4358.3 2152.89  4364.3 2148.37  4398.5 2137.49
  4428.6 2131.87  4491.1 2125.93  4508.9 2124.42  4690.2 2123.68  4789.8 2123.69
  4850.1 2122.20  4921.1 2123.41  4940.4 2123.41  4980.5 2118.43  5053.2 2116.25
  5053.7 2115.75  5074.6 2116.25  5076.6 2118.58  5083.4 2120.83  5093.1 2124.96
  5098.5 2125.15  5184.9 2123.75  5300.0 2126.12  5423.3 2134.03  5488.4 2140.35
  5583.7 2144.01  5589.1 2145.91  5618.4 2147.45  5660.6 2146.50  5742.9 2153.03
#Mann=8,-1,0
  4304.8    0.16       0  4491.1   0.035       0  4690.2    0.07       0
  4789.8    0.16       0  4921.1    0.07       0  5053.2    0.07       0
  5074.6    0.07       0  5083.4    0.16       0
Bank Sta=5053.2,5074.6
Exp/Cntr=0.3,0.1

Type RM Length L Ch R = 1,1385,321,321,321
BEGIN DESCRIPTION:
Little Elm Creek 2 1385.09
END DESCRIPTION:
XS GIS Cut Line= 3
      1509041.28      6775630.30      1509705.31      6775595.72
      1510376.28      6775149.55
#Sta/Elev= 30
  4338.2 2172.67  4351.9 2172.84  4362.0 2170.54  4432.0 2143.59  4482.9 2130.89
  4502.1 2127.84  4539.0 2125.47  4640.2 2122.62  4662.4 2121.48  4852.6 2123.10
  4865.4 2119.51  4932.7 2118.31  4989.8 2114.87  4990.3 2114.37  5011.2 2114.87
  5023.4 2122.45  5029.4 2120.10  5038.5 2123.74  5058.8 2123.49  5291.0 2120.44
  5363.0 2121.35  5492.4 2128.89  5591.6 2137.14  5678.8 2142.03  5729.9 2146.57
  5735.9 2148.32  5750.9 2149.23  5765.9 2147.94  5787.0 2151.42  5808.9 2152.36
#Mann=6,-1,0
  4338.2    0.16       0  4539.0   0.035       0  4640.2    0.07       0
  4989.8    0.07       0  5011.2    0.07       0  5058.8    0.16       0
Bank Sta=4989.8,5011.2
Exp/Cntr=0.3,0.1