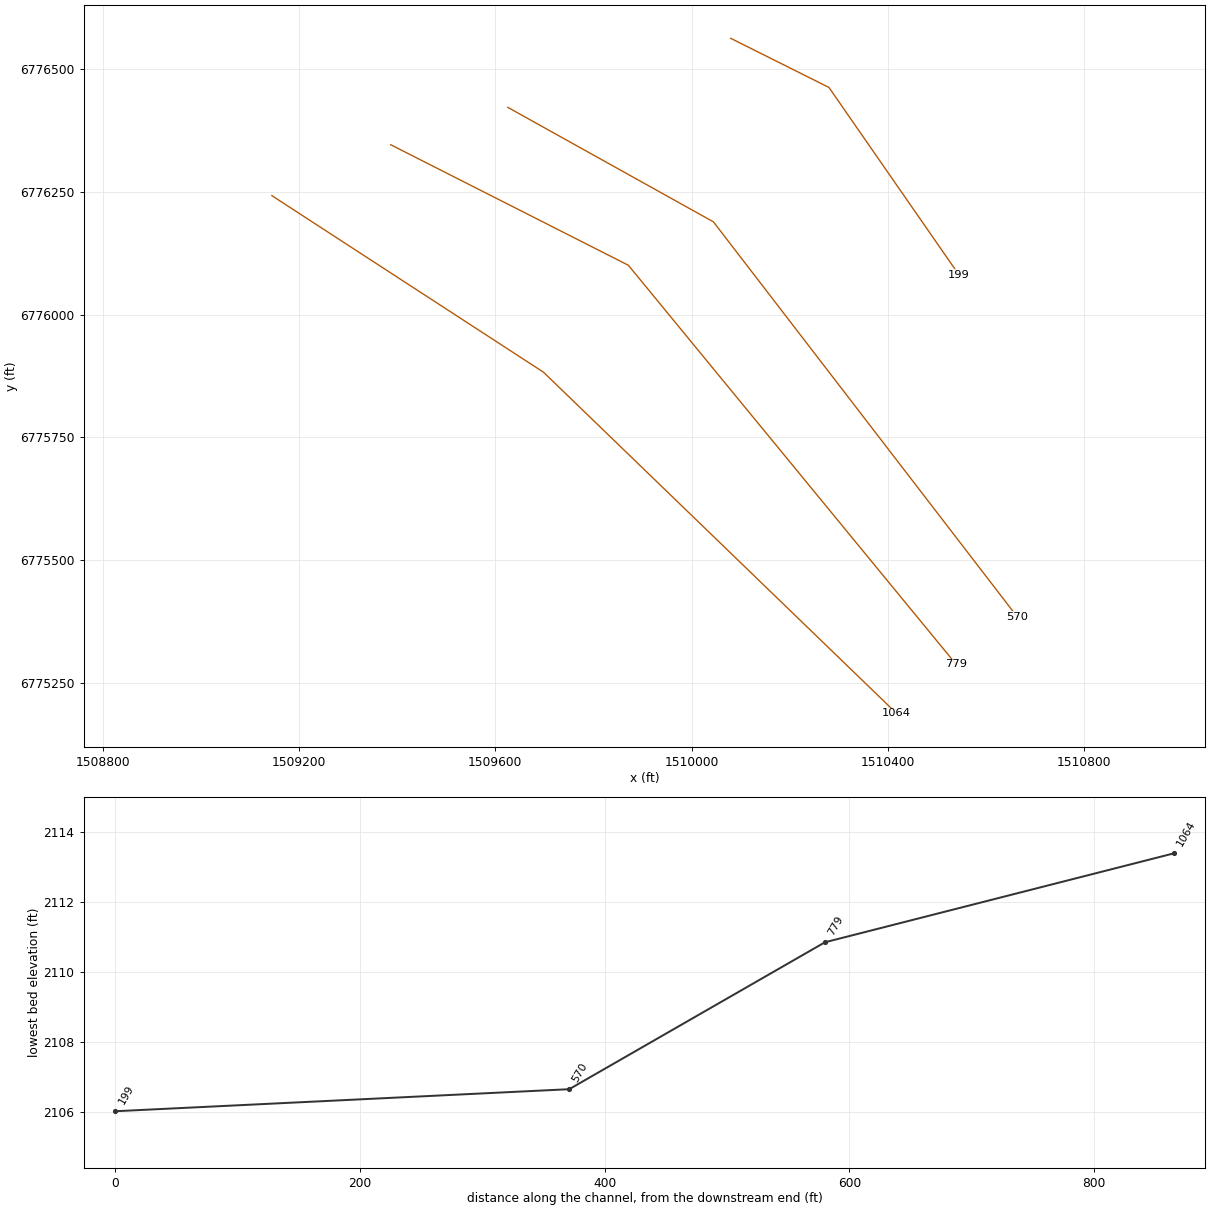
HEC-RAS study Little Elm Creek 2.prj: Little Elm Creek 2 Base Level Engineering

--- Little Elm Creek 2.g01 (geometry) --- (continued)

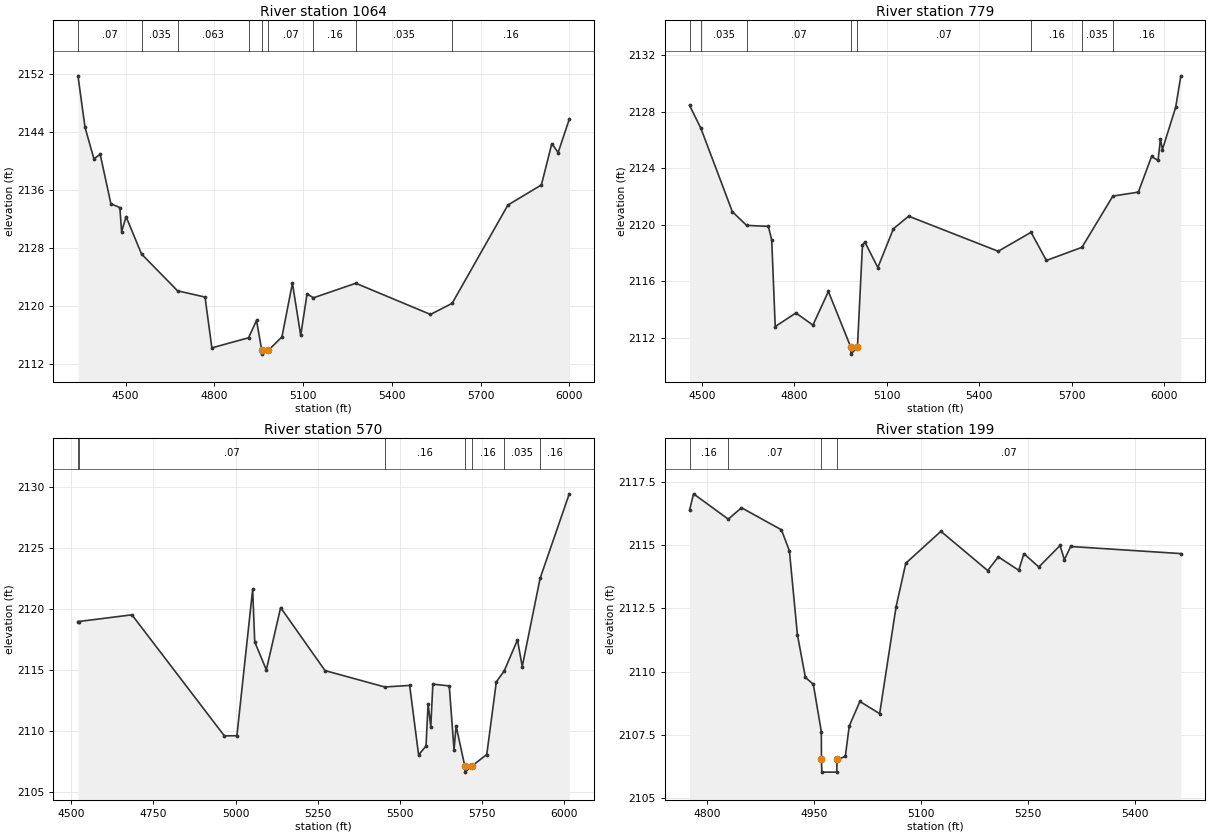
Type RM Length L Ch R = 1,1064,285,285,285
BEGIN DESCRIPTION:
Little Elm Creek 2 1064.25
END DESCRIPTION:
XS GIS Cut Line= 3
      1509145.01      6776242.48      1509698.39      6775882.79
      1510417.78      6775187.61
#Sta/Elev= 30
  4339.1 2151.69  4362.9 2144.60  4393.0 2140.27  4414.1 2140.89  4450.3 2134.09
  4480.6 2133.57  4486.6 2130.25  4501.7 2132.31  4553.9 2127.17  4675.8 2122.11
  4768.5 2121.25  4791.6 2114.26  4915.6 2115.65  4942.5 2118.03  4960.4 2113.90
  4960.9 2113.40  4982.1 2113.90  5028.4 2115.77  5063.9 2123.15  5091.9 2115.98
  5113.3 2121.69  5134.9 2121.15  5278.1 2123.15  5530.5 2118.86  5603.7 2120.39
  5792.1 2133.91  5905.3 2136.68  5940.6 2142.37  5961.9 2141.13  5999.5 2145.72
#Mann=9,-1,0
  4339.1    0.07       0  4553.9   0.035       0  4675.8   0.063       0
  4915.6    0.07       0  4960.4    0.07       0  4982.1    0.07       0
  5134.9    0.16       0  5278.1   0.035       0  5603.7    0.16       0
Bank Sta=4960.4,4982.1
Exp/Cntr=0.3,0.1

Type RM Length L Ch R = 1,779,209,209,209
BEGIN DESCRIPTION:
Little Elm Creek 2 779.21
END DESCRIPTION:
XS GIS Cut Line= 3
      1509387.11      6776346.25      1509871.32      6776100.68
      1510538.86      6775287.89
#Sta/Elev= 30
  4459.6 2128.44  4496.1 2126.83  4598.4 2120.93  4644.7 2119.96  4715.4 2119.89
  4726.3 2118.92  4737.6 2112.81  4804.8 2113.77  4860.0 2112.91  4910.2 2115.29
  4982.8 2111.36  4983.3 2110.86  5004.5 2111.36  5020.8 2118.56  5028.7 2118.78
  5070.7 2116.98  5121.2 2119.72  5170.8 2120.61  5461.4 2118.13  5568.1 2119.47
  5617.8 2117.48  5733.3 2118.41  5833.6 2122.03  5916.3 2122.31  5959.3 2124.83
  5980.2 2124.55  5988.0 2126.04  5994.5 2125.32  6037.5 2128.31  6054.3 2130.53
#Mann=8,-1,0
  4459.6    0.07       0  4496.1   0.035       0  4644.7    0.07       0
  4982.8    0.07       0  5004.5    0.07       0  5568.1    0.16       0
  5733.3   0.035       0  5833.6    0.16       0
Bank Sta=4982.8,5004.5
Exp/Cntr=0.3,0.1

Type RM Length L Ch R = 1,570,371,371,371
BEGIN DESCRIPTION:
Little Elm Creek 2 570.202
END DESCRIPTION:
XS GIS Cut Line= 3
      1509625.73      6776422.36      1510044.67      6776189.10
      1510663.37      6775384.73
#Sta/Elev= 30
  4520.5 2118.97  4522.2 2118.97  4684.6 2119.52  4965.9 2109.62  5003.9 2109.64
  5051.8 2121.60  5058.1 2117.31  5093.4 2115.02  5136.9 2120.11  5271.9 2114.96
  5453.8 2113.62  5529.3 2113.75  5556.5 2108.07  5579.1 2108.79  5585.4 2112.25
  5593.6 2110.37  5599.9 2113.85  5649.8 2113.71  5664.3 2108.47  5670.6 2110.44
  5697.0 2107.16  5697.5 2106.66  5718.7 2107.16  5763.9 2108.10  5793.0 2114.04
  5816.9 2114.93  5857.3 2117.47  5871.8 2115.29  5926.1 2122.50  6014.8 2129.41
#Mann=7,-1,0
  4520.5   0.035       0  4522.2    0.07       0  5453.8    0.16       0
  5697.0    0.07       0  5718.7    0.16       0  5816.9   0.035       0
  5926.1    0.16       0
Bank Sta=5697,5718.7
Exp/Cntr=0.3,0.1

Type RM Length L Ch R = 1,199,0,0,0
BEGIN DESCRIPTION:
Little Elm Creek 2 199.224
END DESCRIPTION:
XS GIS Cut Line= 3
      1510079.96      6776563.02      1510280.00      6776463.00
      1510544.69      6776081.48
#Sta/Elev= 30
  4776.0 2116.38  4781.6 2117.02  4830.2 2116.02  4848.7 2116.47  4904.6 2115.60
  4915.8 2114.77  4927.0 2111.46  4938.2 2109.77  4949.3 2109.50  4960.5 2107.63
  4960.7 2106.53  4961.2 2106.03  4982.1 2106.03  4982.6 2106.53  4994.1 2106.65
  4999.6 2107.85  5014.5 2108.82  5042.2 2108.34  5065.2 2112.56  5078.8 2114.28
  5128.0 2115.54  5193.5 2113.99  5208.4 2114.53  5237.0 2114.00  5244.2 2114.66
  5265.1 2114.13  5294.8 2114.98  5300.9 2114.42  5309.7 2114.94  5464.0 2114.66
#Mann=4,-1,0
  4776.0    0.16       0  4830.2    0.07       0  4960.7    0.07       0
  4982.6    0.07       0
Bank Sta=4960.7,4982.6
Exp/Cntr=0.3,0.1

Chan Stop Cuts=-1