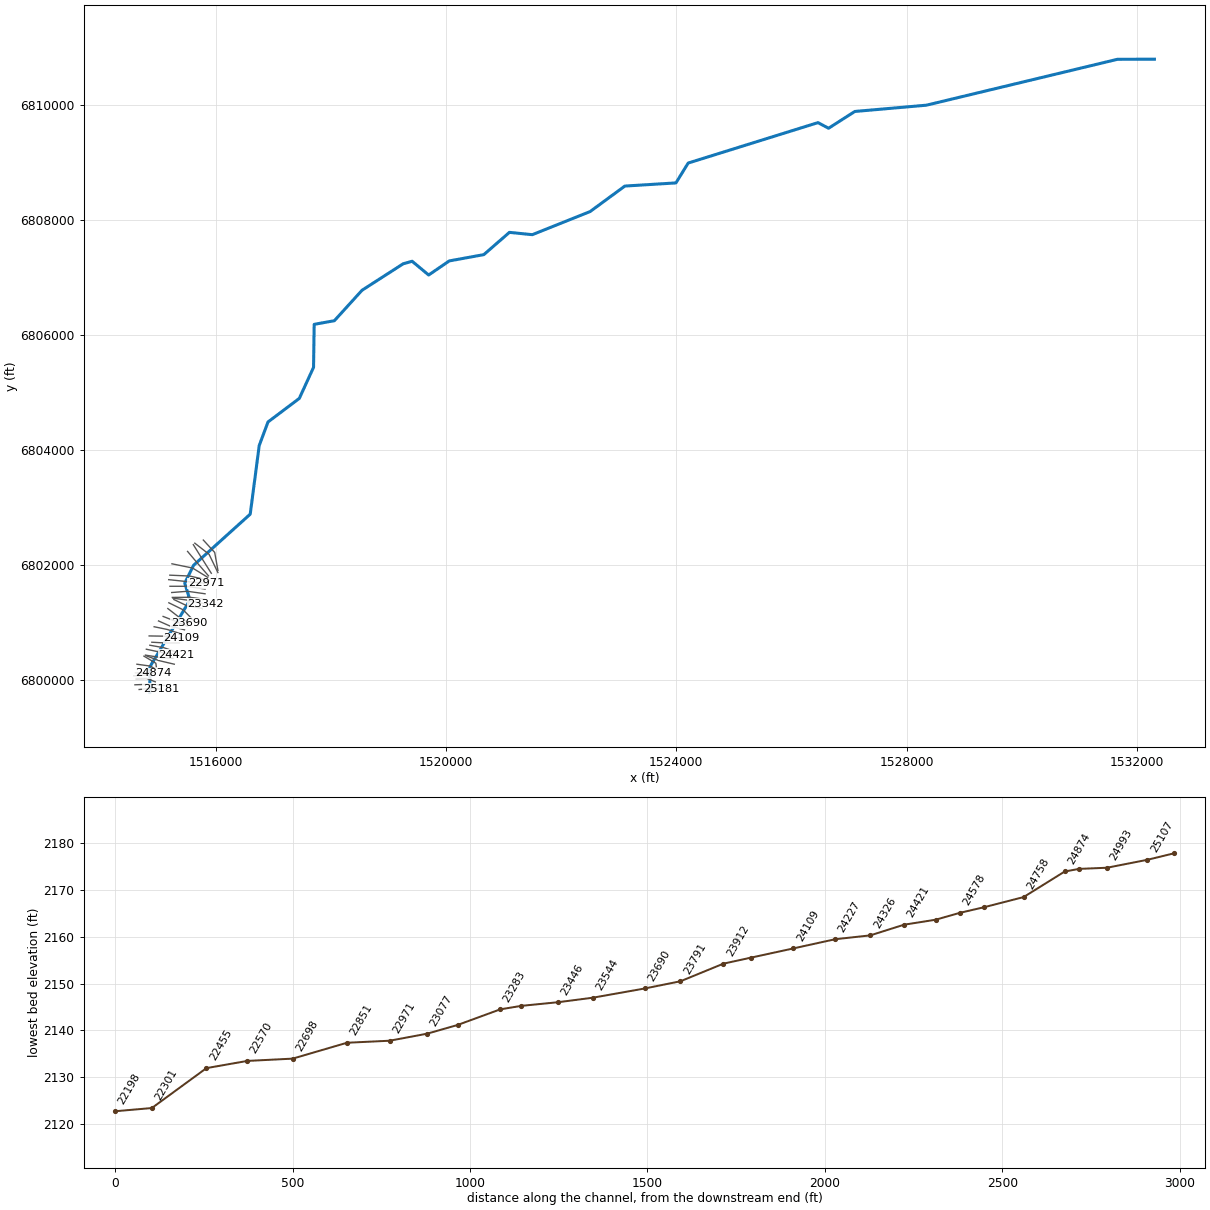
--- Little Elm Creek A.prj (project) ---

Proj Title=Little Elm Creek A Base Level Engineering
Current Plan=p01
Default Exp/Contr=0.3,0.1
English Units
Geom File=g01
Flow File=f01
Flow File=f02
Flow File=f03
Plan File=p01
Y Axis Title=Elevation
X Axis Title(PF)=Main Channel Distance
X Axis Title(XS)=Station
BEGIN DESCRIPTION:
Little Elm Creek A
END DESCRIPTION:
DSS Export Rating Curves= 0
DSS Export Rating Curve Sorted= 0
DSS Export Volume Flow Curves= 0
DXF OffsetX= 0
DXF OffsetY= 0
DXF ScaleX= 1
DXF ScaleY= 10

--- Little Elm Creek A.p01 (plan) ---

Plan Title=Multiple Run
Program Version=4.10
Short Identifier=Multiple
Geom File=g01
Flow File=f01
Subcritical Flow
K Sum by GR= 0
Std Step Tol= 0.01
Critical Tol= 0.01
Num of Std Step Trials= 20
Max Error Tol= 0.3
Flow Tol Ratio= 0.001
Split Flow NTrial= 30
Split Flow Tol= 0.02
Split Flow Ratio= 0.02
Log Output Level= 0
Friction Slope Method= 1
Unsteady Friction Slope Method= 2
Unsteady Bridges Friction Slope Method= 1
Parabolic Critical Depth
Global Vel Dist= 1 , 1 , 1
Global Log Level= 0
CheckData=True
Encroach Param=-1 ,0,0, 0
BEGIN DESCRIPTION:
Multiple Run
END DESCRIPTION:
Computation Interval=1HOUR
Output Interval=1HOUR
Run HTab= 0
Run UNet= 0
Run PostProcess= 0
Run WQNet= 0
UNET Theta= 1
UNET Theta Warmup= 1
UNET ZTol= 0.02
UNET ZSATol= 0.05
UNET MxIter= 20
UNET MaxInSteps= 0
UNET DtIC= 0
UNET DtMin= 0
UNET MaxCRTS= 20
UNET WFStab= 2
UNET SFStab= 1
UNET WFX= 1
UNET SFX= 1
UNET DSS MLevel= 4
UNET DZMax Abort= 100
UNET Convert EG Bridges= 0
UNET Use Existing IB Tables=-1
UNET Froude Reduction=False
UNET Froude Limit= 1
UNET Froude Power= 10
UNET Time Slicing=0,0, 5
UNET Junction Losses=0
Instantaneous Interval=1HOUR
Write IC File= 0
Write IC File at Sim End=0
Echo Input=False
Echo Parameters=False
Echo Output=False
Write Detailed= 0
WQ AD Non Conservative
WQ ULTIMATE=-1
WQ Max Comp Step=1HOUR
WQ Output Interval=15MIN
WQ Output Selected Increments= 0
WQ Output face flow=0
WQ Output face velocity=0
WQ Output face area=0
WQ Output face dispersion=0
WQ Output cell volume=0
WQ Output cell surface area=0
WQ Output cell continuity=0
WQ Output cumulative cell continuity=0
WQ Output face conc=0
WQ Output face dconc_dx=0
WQ Output face courant=0
WQ Output face peclet=0
WQ Output face adv mass=0
WQ Output face disp mass=0
WQ Output cell mass=0
WQ Output cell source sink temp=0
WQ Output cell source sink nsm=0
WQ Output MaxMinRange=-1
WQ Daily Max Min Mean=-1
WQ Daily Range=0
WQ Daily Time=0
WQ Create Restart=0
WQ Fixed Restart=0
WQ System Summary=0
WQ Use Fixed Temperature=0
Sorting and Armoring Iterations= 10
XS Update Threshold= 0.02
Hydraulics Update Threshold= 0.02
Energy Slope Method= 1
Volume Change Method= 0
XS Weighting Method= 0
Number of US Weighted Cross Sections= 1
Number of DS Weighted Cross Sections= 1
Upstream XS Weight=0.25
Main XS Weight=0.5
Downstream XS Weight=0.25
Number of DS XS's Weighted with US Boundary= 1
Upstream Boundary Weight= 1
Weight of XSs Associated with US Boundary= 0
Number of US XS's Weighted with DS Boundary= 1
Downstream Boundary Weight= 0.5
Weight of XSs Associated with DS Boundary= 0.5
Sediment Output Level= 4
Mass or Volume Output= 0
Output Increment Type= 1
Profile and TS Output Increment= 10
XS Output Flag= 0
XS Output Increment= 10
Disregard all LS=0
Disregard all Conn=0
Disregard all Breaches=0
Disregard all Pumps=0

--- Little Elm Creek A.f01 (steady flow) ---

Flow Title=Multiple
Number of Profiles=7
Profile Names=10-year,25-year,50-year,1pct_min,100-year,1pct_plu,500-year
River Rch & RM= Little Elm Creek,Reach-1,25181
     400     583     743     588     942    1300    1540
River Rch & RM= Little Elm Creek,Reach-1,23446
     471     691     885     703    1130    1550    1850
River Rch & RM= Little Elm Creek,Reach-1,16656
     775    1160    1510    1210    1940    2660    3250
River Rch & RM= Little Elm Creek,Reach-1,7006
     837    1250    1620    1300    2090    2870    3490
Boundary for River Rch & Prof#=Little Elm Creek,Reach-1,1
Up Type=0
Dn Type=3
Dn Slope=0.02
Boundary for River Rch & Prof#=Little Elm Creek,Reach-1,2
Up Type=0
Dn Type=3
Dn Slope=0.02
Boundary for River Rch & Prof#=Little Elm Creek,Reach-1,3
Up Type=0
Dn Type=3
Dn Slope=0.02
Boundary for River Rch & Prof#=Little Elm Creek,Reach-1,4
Up Type=0
Dn Type=3
Dn Slope=0.02
Boundary for River Rch & Prof#=Little Elm Creek,Reach-1,5
Up Type=0
Dn Type=3
Dn Slope=0.02
Boundary for River Rch & Prof#=Little Elm Creek,Reach-1,6
Up Type=0
Dn Type=3
Dn Slope=0.02
Boundary for River Rch & Prof#=Little Elm Creek,Reach-1,7
Up Type=0
Dn Type=3
Dn Slope=0.02

--- Little Elm Creek A.g01 (geometry) ---

Geom Title=Existing Conditions

River Reach=Little Elm Creek,Reach-1
Reach XY= 30
      1514855.00      6799788.00      1514858.45      6800236.75
      1515552.86      6801393.97      1515462.33      6801688.10
      1515615.76      6801997.68      1516599.54      6802885.55
      1516755.75      6804077.31      1516908.16      6804486.35
      1517451.94      6804896.28      1517699.53      6805435.55
      1517710.41      6806182.82      1518061.19      6806245.82
      1518541.76      6806774.88      1519256.50      6807234.39
      1519411.62      6807278.59      1519698.95      6807039.58
      1520056.55      6807284.25      1520657.39      6807393.69
      1521101.67      6807780.39      1521499.14      6807740.07
      1522503.44      6808141.76      1523106.47      6808584.45
      1523994.02      6808639.25      1524206.56      6808984.24
      1526461.05      6809686.41      1526645.14      6809588.86
      1527101.34      6809880.28      1528345.29      6809989.27
      1531664.71      6810786.74      1532305.00      6810788.00

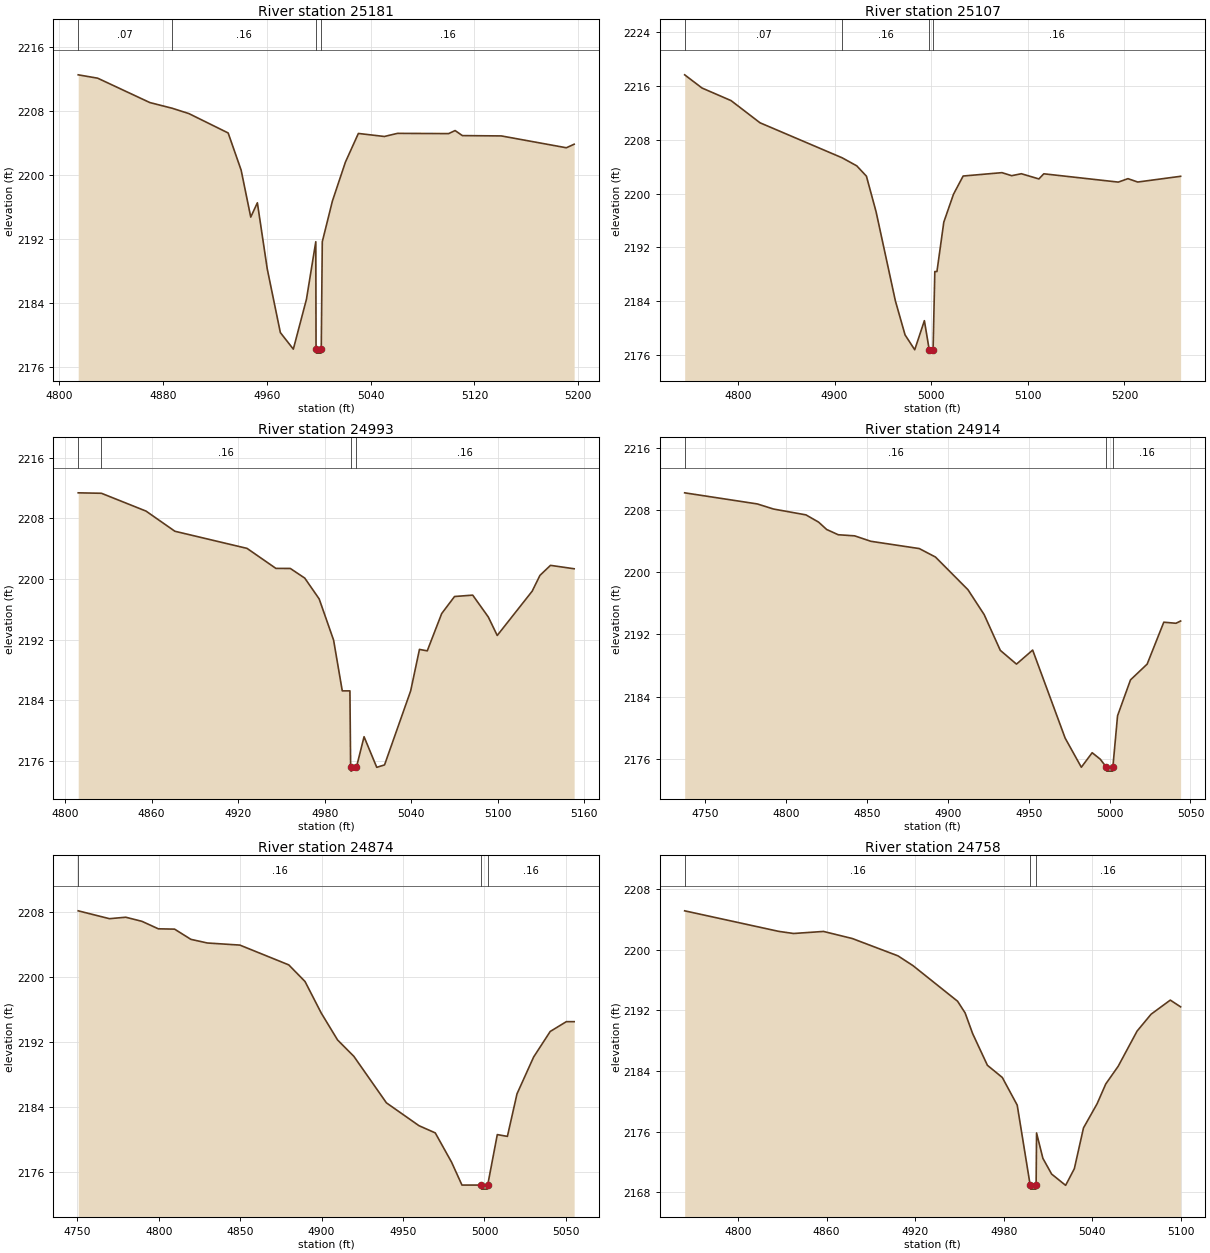
Type RM Length L Ch R = 1,25181,74,74,74
BEGIN DESCRIPTION:
Little Elm Creek A 25181.227
END DESCRIPTION:
XS GIS Cut Line= 3
      1514670.05      6799840.07      1514854.41      6799857.76
      1515051.00      6799848.79
#Sta/Elev= 30
  4814.8 2212.50  4829.8 2212.08  4870.0 2209.03  4887.2 2208.32  4900.1 2207.65
  4930.3 2205.23  4940.3 2200.58  4947.7 2194.71  4952.8 2196.50  4960.4 2188.24
  4970.5 2180.27  4980.5 2178.20  4990.6 2184.43  4997.8 2191.63  4998.0 2178.20
  4998.3 2177.70  5001.8 2177.70  5002.0 2178.20  5002.8 2191.63  5010.6 2196.72
  5020.6 2201.58  5030.6 2205.17  5050.6 2204.79  5060.7 2205.18  5100.1 2205.15
  5105.1 2205.53  5110.7 2204.90  5140.7 2204.86  5190.8 2203.38  5196.8 2203.82
#Mann=4,-1,0
  4814.8    0.07       0  4887.2    0.16       0  4998.0    0.07       0
  5002.0    0.16       0
Bank Sta=4998,5002
Exp/Cntr=0.3,0.1

Type RM Length L Ch R = 1,25107,114,114,114
BEGIN DESCRIPTION:
Little Elm Creek A 25106.68
END DESCRIPTION:
XS GIS Cut Line= 3
      1514597.06      6799921.66      1514855.79      6799932.08
      1515109.30      6799911.24
#Sta/Elev= 30
  4744.9 2217.59  4762.9 2215.63  4792.9 2213.77  4822.9 2210.48  4907.9 2205.29
  4923.0 2204.10  4933.0 2202.57  4943.0 2197.30  4963.0 2184.08  4973.0 2179.04
  4983.0 2176.84  4993.0 2181.15  4998.0 2176.84  4998.3 2176.34  5001.8 2176.34
  5002.0 2176.84  5003.8 2188.43  5006.0 2188.43  5013.1 2195.76  5023.1 2199.88
  5033.1 2202.59  5073.3 2203.09  5083.3 2202.64  5093.4 2202.93  5111.5 2202.16
  5116.6 2202.92  5193.7 2201.69  5203.7 2202.20  5213.8 2201.70  5258.2 2202.55
#Mann=4,-1,0
  4744.9    0.07       0  4907.9    0.16       0  4998.0    0.07       0
  5002.0    0.16       0
Bank Sta=4998,5002
Exp/Cntr=0.3,0.1

Type RM Length L Ch R = 1,24993,79,79,79
BEGIN DESCRIPTION:
Little Elm Creek A 24991.33
END DESCRIPTION:
XS GIS Cut Line= 3
      1514617.96      6800031.04      1514801.97      6800032.77
      1514950.25      6799973.52
#Sta/Elev= 30
  4809.2 2211.37  4825.3 2211.31  4856.2 2208.96  4876.2 2206.30  4926.2 2204.04
  4946.2 2201.40  4956.2 2201.39  4966.2 2200.12  4976.2 2197.37  4986.2 2191.93
  4992.2 2185.24  4997.5 2185.24  4998.0 2175.15  4998.3 2174.65  5002.0 2175.15
  5007.3 2179.19  5016.1 2175.15  5021.5 2175.47  5039.6 2185.24  5045.7 2190.71
  5051.1 2190.52  5061.1 2195.44  5070.0 2197.69  5082.6 2197.87  5093.4 2194.99
  5099.6 2192.55  5123.8 2198.39  5129.2 2200.48  5136.5 2201.80  5152.9 2201.35
#Mann=4,-1,0
  4809.2    0.07       0  4825.3    0.16       0  4998.0    0.07       0
  5002.0    0.16       0
Bank Sta=4998,5002
Exp/Cntr=0.3,0.1

Type RM Length L Ch R = 1,24914,40,40,40
BEGIN DESCRIPTION:
Little Elm Creek A 24914.26
END DESCRIPTION:
XS GIS Cut Line= 3
      1514590.14      6800077.91      1514852.32      6800093.54
      1514895.06      6800082.86
#Sta/Elev= 30
  4737.2 2210.24  4782.1 2208.81  4792.2 2208.15  4812.2 2207.40  4820.0 2206.47
  4825.0 2205.52  4832.2 2204.84  4842.3 2204.70  4852.3 2204.00  4882.3 2203.06
  4892.3 2201.97  4912.4 2197.76  4922.4 2194.56  4932.4 2189.95  4942.4 2188.18
  4952.4 2189.99  4972.5 2178.65  4982.5 2174.90  4989.2 2176.77  4994.2 2175.94
  4998.0 2174.90  4998.3 2174.40  5001.8 2174.40  5002.0 2174.90  5004.9 2181.53
  5012.9 2186.15  5023.2 2188.18  5033.5 2193.58  5041.0 2193.44  5043.9 2193.73
#Mann=3,-1,0
  4737.2    0.16       0  4998.0    0.07       0  5002.0    0.16       0
Bank Sta=4998,5002
Exp/Cntr=0.3,0.1

Type RM Length L Ch R = 1,24874,116,116,116
BEGIN DESCRIPTION:
Little Elm Creek A 24874.31
END DESCRIPTION:
XS GIS Cut Line= 3
      1514605.76      6800128.26      1514866.20      6800133.47
      1514909.41      6800124.59
#Sta/Elev= 30
  4750.5 2208.20  4769.7 2207.23  4779.7 2207.41  4789.7 2206.90  4799.7 2205.98
  4809.7 2205.94  4819.7 2204.68  4829.8 2204.23  4849.8 2203.97  4879.8 2201.53
  4889.8 2199.48  4899.8 2195.57  4909.8 2192.26  4919.8 2190.24  4939.8 2184.50
  4959.8 2181.68  4969.8 2180.79  4979.8 2177.18  4986.2 2174.35  4998.0 2174.35
  4998.3 2173.85  5001.8 2173.85  5002.0 2174.35  5007.9 2180.58  5014.1 2180.36
  5020.0 2185.61  5030.2 2190.15  5040.4 2193.31  5050.3 2194.52  5055.1 2194.52
#Mann=3,-1,0
  4750.5    0.16       0  4998.0    0.07       0  5002.0    0.16       0
Bank Sta=4998,5002
Exp/Cntr=0.3,0.1

Type RM Length L Ch R = 1,24758,111,111,111
BEGIN DESCRIPTION:
Little Elm Creek A 24758.25
END DESCRIPTION:
XS GIS Cut Line= 3
      1514631.87      6800279.30      1514867.94      6800246.32
      1514951.00      6800194.98
#Sta/Elev= 30
  4763.9 2205.12  4827.6 2202.41  4837.7 2202.13  4857.9 2202.40  4877.4 2201.47
  4908.4 2199.18  4918.5 2197.90  4948.8 2193.19  4953.9 2191.65  4959.0 2188.92
  4969.0 2184.74  4979.1 2183.13  4989.2 2179.48  4998.0 2168.90  4998.3 2168.40
  5001.8 2168.40  5002.0 2168.90  5002.3 2175.81  5006.6 2172.46  5012.5 2170.39
  5022.0 2168.90  5027.9 2171.10  5034.1 2176.48  5043.3 2179.66  5049.2 2182.28
  5057.6 2184.61  5070.4 2189.25  5079.9 2191.48  5092.9 2193.34  5099.9 2192.45
#Mann=3,-1,0
  4763.9    0.16       0  4998.0    0.07       0  5002.0    0.16       0
Bank Sta=4998,5002
Exp/Cntr=0.3,0.1

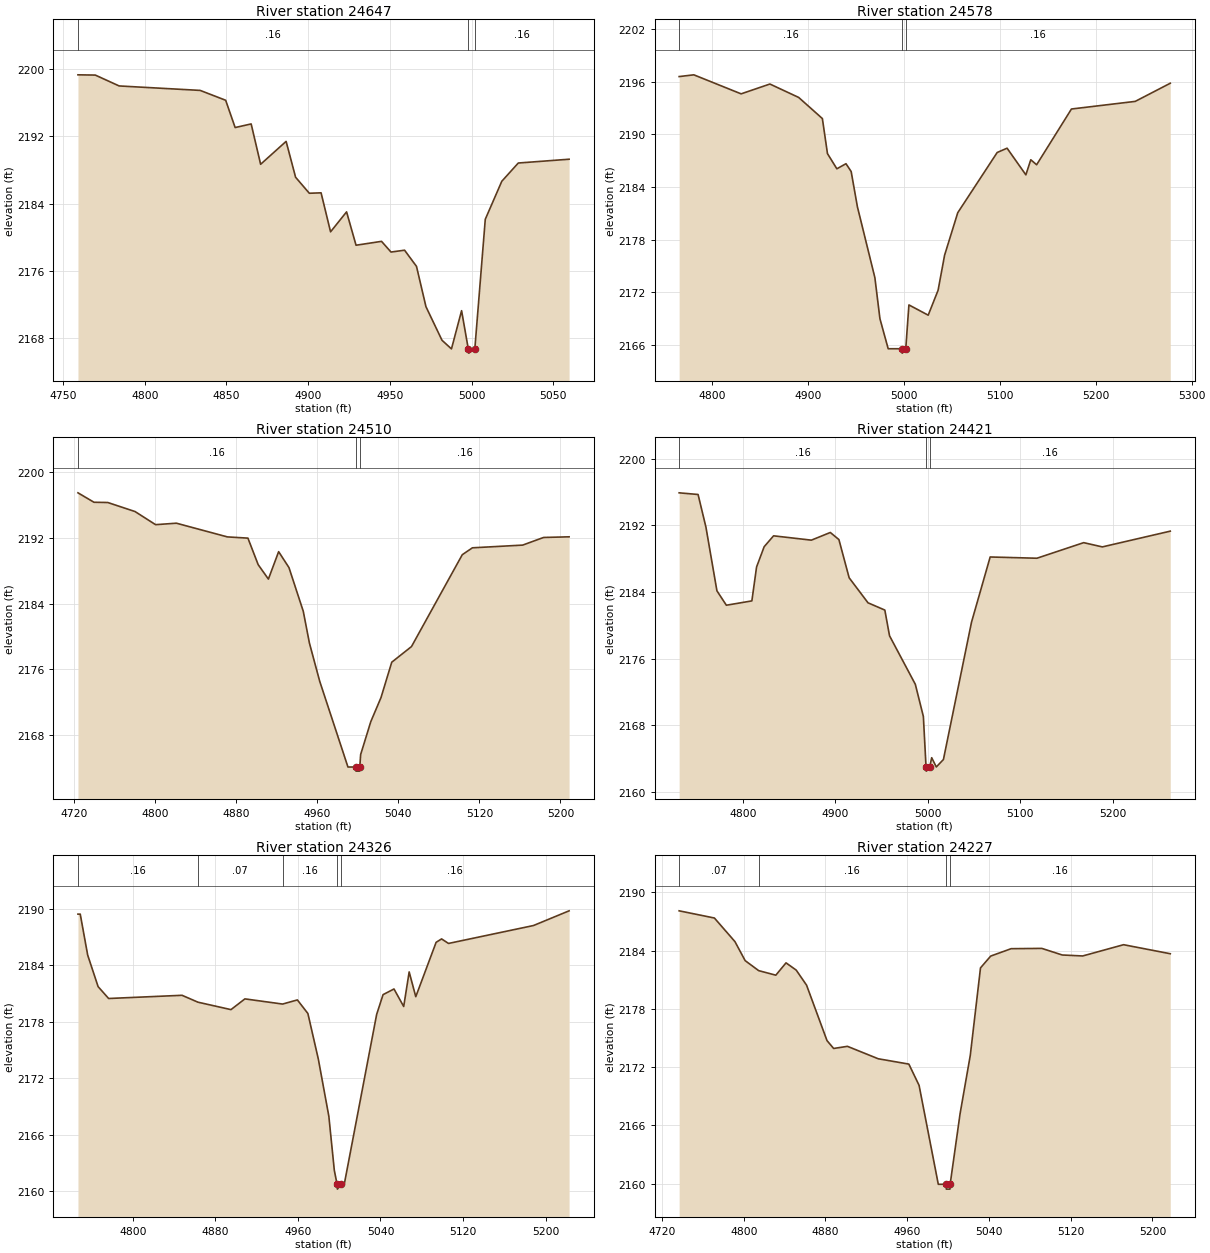
Type RM Length L Ch R = 1,24647,69,69,69
BEGIN DESCRIPTION:
Little Elm Creek A 24646.79
END DESCRIPTION:
XS GIS Cut Line= 3
      1514753.37      6800419.92      1514959.95      6800296.66
      1514968.30      6800237.21
#Sta/Elev= 30
  4759.1 2199.29  4769.7 2199.26  4784.3 2197.97  4833.9 2197.44  4849.5 2196.27
  4855.3 2193.03  4865.1 2193.46  4870.9 2188.67  4886.5 2191.39  4892.3 2187.13
  4900.7 2185.23  4907.9 2185.28  4913.7 2180.65  4923.5 2183.02  4929.3 2179.06
  4944.9 2179.52  4950.7 2178.25  4959.0 2178.47  4966.3 2176.55  4972.1 2171.76
  4981.9 2167.78  4987.7 2166.75  4993.9 2171.29  4998.0 2166.75  4998.3 2166.25
  5002.0 2166.75  5008.4 2182.14  5018.5 2186.65  5028.6 2188.82  5059.7 2189.27
#Mann=3,-1,0
  4759.1    0.16       0  4998.0    0.07       0  5002.0    0.16       0
Bank Sta=4998,5002
Exp/Cntr=0.3,0.1

Type RM Length L Ch R = 1,24578,68,68,68
BEGIN DESCRIPTION:
Little Elm Creek A 24578.18
END DESCRIPTION:
XS GIS Cut Line= 3
      1514791.56      6800426.87      1515008.57      6800343.54
      1515280.56      6800279.44
#Sta/Elev= 30
  4765.8 2196.59  4781.1 2196.79  4830.4 2194.62  4860.4 2195.74  4890.4 2194.21
  4915.1 2191.80  4920.4 2187.80  4930.2 2186.07  4939.7 2186.65  4945.1 2185.76
  4951.6 2181.74  4969.8 2173.66  4975.1 2168.96  4983.7 2165.54  4998.0 2165.54
  4998.3 2165.04  5002.0 2165.54  5005.3 2170.54  5025.4 2169.37  5035.7 2172.21
  5042.5 2176.22  5056.2 2181.06  5097.3 2187.93  5107.6 2188.42  5127.2 2185.38
  5132.3 2187.10  5138.4 2186.53  5174.7 2192.89  5241.2 2193.76  5277.7 2195.83
#Mann=3,-1,0
  4765.8    0.16       0  4998.0    0.07       0  5002.0    0.16       0
Bank Sta=4998,5002
Exp/Cntr=0.3,0.1

Type RM Length L Ch R = 1,24510,89,89,89
BEGIN DESCRIPTION:
Little Elm Creek A 24510.4
END DESCRIPTION:
XS GIS Cut Line= 3
      1514779.35      6800437.30      1515045.02      6800395.62
      1515260.14      6800380.01
#Sta/Elev= 30
  4723.9 2197.49  4739.7 2196.34  4753.3 2196.31  4780.2 2195.21  4800.5 2193.61
  4821.0 2193.79  4871.3 2192.12  4891.6 2191.97  4901.7 2188.74  4911.8 2186.98
  4921.9 2190.32  4932.1 2188.38  4946.2 2183.06  4952.3 2179.17  4962.4 2174.54
  4990.3 2164.08  4998.0 2164.08  4998.3 2163.58  5001.8 2163.58  5002.0 2164.08
  5002.8 2165.59  5012.8 2169.60  5022.9 2172.54  5033.5 2176.85  5053.0 2178.76
  5103.1 2189.95  5113.1 2190.79  5162.7 2191.12  5183.3 2192.05  5208.5 2192.13
#Mann=3,-1,0
  4723.9    0.16       0  4998.0    0.07       0  5002.0    0.16       0
Bank Sta=4998,5002
Exp/Cntr=0.3,0.1

Type RM Length L Ch R = 1,24421,95,95,95
BEGIN DESCRIPTION:
Little Elm Creek A 24420.9
END DESCRIPTION:
XS GIS Cut Line= 3
      1514794.99      6800539.73      1515057.18      6800484.16
      1515317.63      6800444.23
#Sta/Elev= 30
  4730.8 2195.92  4751.3 2195.72  4759.8 2191.80  4771.7 2184.16  4781.9 2182.43
  4809.5 2182.95  4814.6 2187.02  4822.8 2189.45  4833.0 2190.76  4873.9 2190.24
  4894.4 2191.16  4903.7 2190.31  4914.8 2185.72  4935.2 2182.72  4953.4 2181.85
  4958.5 2178.76  4986.4 2172.94  4995.1 2169.08  4998.0 2163.02  4998.3 2162.52
  5002.0 2163.02  5004.1 2164.13  5009.1 2163.02  5016.8 2163.91  5047.2 2180.39
  5067.4 2188.22  5118.0 2188.07  5168.6 2189.94  5188.8 2189.43  5262.3 2191.32
#Mann=3,-1,0
  4730.8    0.16       0  4998.0    0.07       0  5002.0    0.16       0
Bank Sta=4998,5002
Exp/Cntr=0.3,0.1

Type RM Length L Ch R = 1,24326,99,99,99
BEGIN DESCRIPTION:
Little Elm Creek A 24325.68
END DESCRIPTION:
XS GIS Cut Line= 3
      1514855.76      6800609.17      1515100.58      6800565.76
      1515315.64      6800492.92
#Sta/Elev= 30
  4747.0 2189.42  4749.2 2189.42  4756.4 2185.08  4766.5 2181.73  4776.7 2180.47
  4847.8 2180.81  4863.2 2180.08  4895.2 2179.29  4908.7 2180.43  4945.2 2179.88
  4959.5 2180.32  4969.7 2178.88  4979.8 2174.05  4990.0 2167.98  4995.3 2162.24
  4998.0 2160.75  4998.3 2160.25  5002.0 2160.75  5004.9 2160.75  5036.3 2178.78
  5042.5 2180.88  5053.1 2181.48  5062.5 2179.62  5067.8 2183.29  5074.2 2180.66
  5093.9 2186.43  5099.2 2186.79  5105.9 2186.31  5188.2 2188.21  5222.7 2189.77
#Mann=5,-1,0
  4747.0    0.16       0  4863.2    0.07       0  4945.2    0.16       0
  4998.0    0.07       0  5002.0    0.16       0
Bank Sta=4998,5002
Exp/Cntr=0.3,0.1

Type RM Length L Ch R = 1,24227,118,118,118
BEGIN DESCRIPTION:
Little Elm Creek A 24227.34
END DESCRIPTION:
XS GIS Cut Line= 3
      1514890.52      6800661.25      1515147.45      6800647.36
      1515370.74      6800649.09
#Sta/Elev= 30
  4736.8 2188.10  4771.3 2187.36  4791.4 2184.93  4801.4 2182.97  4814.6 2181.94
  4831.4 2181.47  4841.4 2182.74  4851.4 2181.99  4861.5 2180.44  4881.5 2174.73
  4888.0 2173.92  4901.5 2174.14  4931.6 2172.86  4961.6 2172.31  4971.6 2170.12
  4990.4 2159.93  4998.0 2159.93  4998.3 2159.43  5001.8 2159.43  5002.0 2159.93
  5011.7 2167.19  5021.7 2173.21  5031.7 2182.22  5041.7 2183.44  5061.7 2184.20
  5091.7 2184.23  5111.7 2183.55  5131.7 2183.45  5171.7 2184.61  5217.4 2183.68
#Mann=4,-1,0
  4736.8    0.07       0  4814.6    0.16       0  4998.0    0.07       0
  5002.0    0.16       0
Bank Sta=4998,5002
Exp/Cntr=0.3,0.1

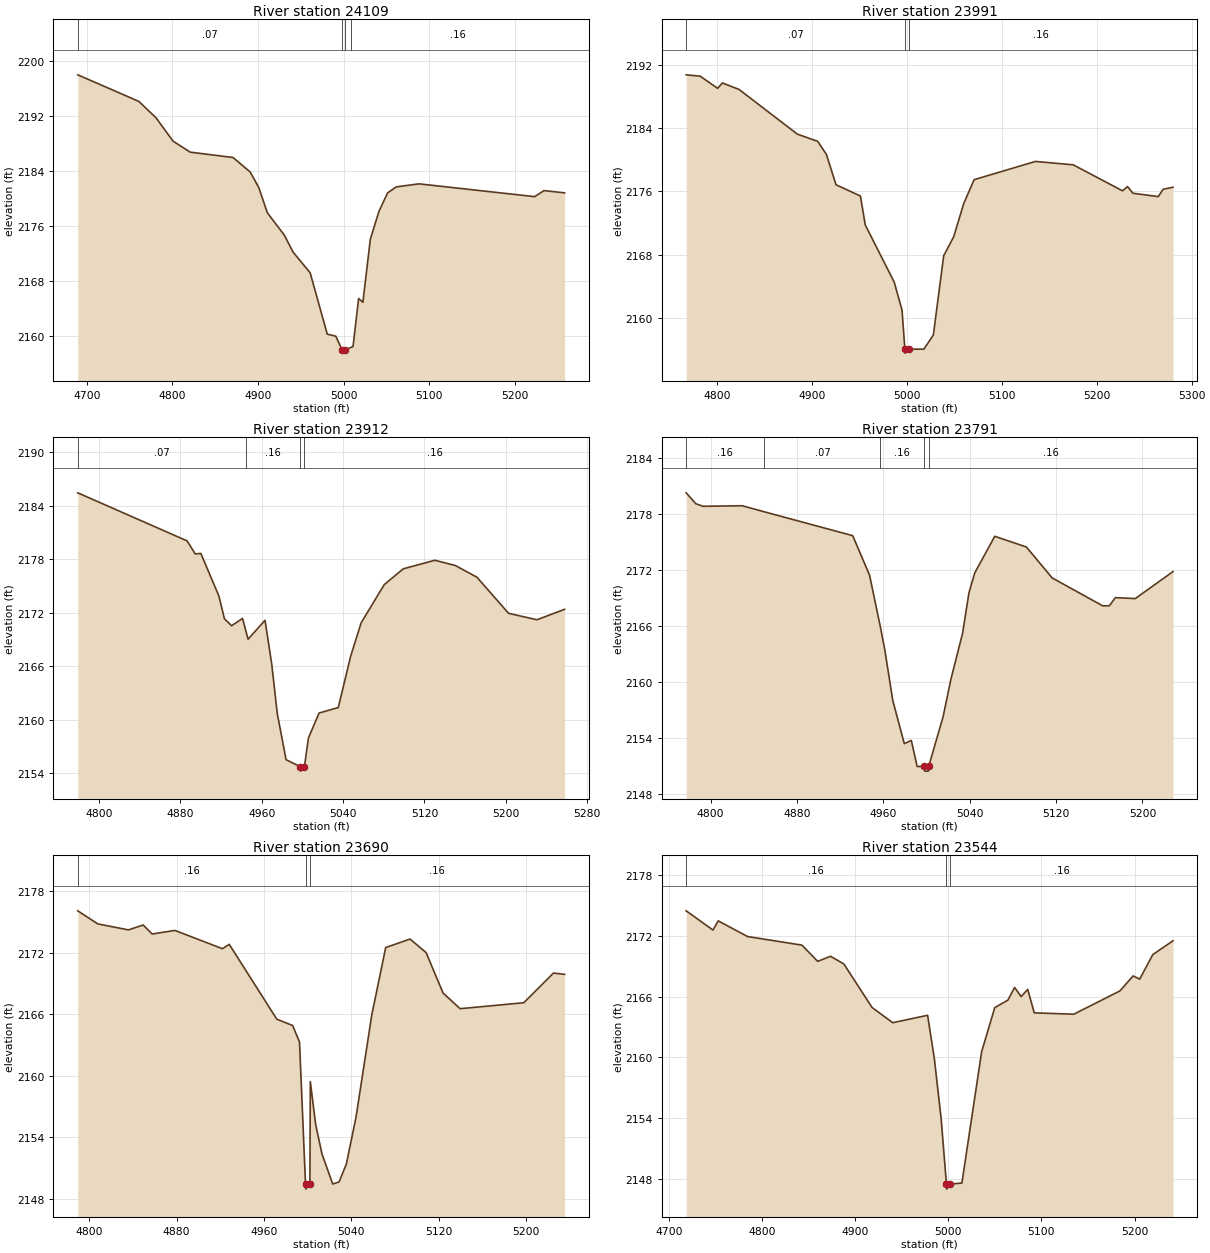
Type RM Length L Ch R = 1,24109,118,118,118
BEGIN DESCRIPTION:
Little Elm Creek A 24109.21
END DESCRIPTION:
XS GIS Cut Line= 3
      1514843.67      6800770.62      1515156.14      6800765.41
      1515409.62      6800728.95
#Sta/Elev= 30
  4689.4 2197.93  4760.7 2194.07  4780.7 2191.70  4800.7 2188.29  4820.7 2186.69
  4870.8 2185.91  4890.8 2183.80  4900.8 2181.55  4910.8 2177.88  4930.8 2174.60
  4940.8 2172.17  4960.8 2169.15  4980.8 2160.23  4990.8 2159.93  4998.0 2157.97
  4998.3 2157.47  5001.8 2157.47  5002.0 2157.97  5009.0 2158.33  5010.9 2158.43
  5017.4 2165.41  5022.4 2164.86  5031.1 2174.03  5041.2 2178.09  5051.3 2180.77
  5061.4 2181.64  5087.9 2182.08  5223.0 2180.22  5233.9 2181.10  5258.0 2180.77
#Mann=4,-1,0
  4689.4    0.07       0  4998.0    0.07       0  5002.0    0.07       0
  5009.0    0.16       0
Bank Sta=4998,5002
Exp/Cntr=0.3,0.1

Type RM Length L Ch R = 1,23991,79,79,79
BEGIN DESCRIPTION:
Little Elm Creek A 23991.37
END DESCRIPTION:
XS GIS Cut Line= 3
      1514930.48      6800930.34      1515156.14      6800883.47
      1515425.24      6800798.40
#Sta/Elev= 30
  4767.7 2190.75  4782.5 2190.58  4800.8 2189.04  4805.9 2189.72  4823.4 2188.90
  4884.7 2183.25  4906.2 2182.33  4915.3 2180.70  4925.5 2176.84  4951.2 2175.41
  4956.3 2171.75  4986.8 2164.51  4995.0 2160.97  4998.0 2156.03  4998.3 2155.53
  5002.0 2156.03  5018.0 2156.03  5028.0 2157.83  5038.9 2167.86  5049.4 2170.25
  5059.9 2174.43  5070.9 2177.48  5135.5 2179.79  5175.3 2179.36  5227.2 2176.07
  5232.5 2176.61  5238.2 2175.76  5264.8 2175.34  5270.0 2176.27  5280.4 2176.52
#Mann=3,-1,0
  4767.7    0.07       0  4998.0    0.07       0  5002.0    0.16       0
Bank Sta=4998,5002
Exp/Cntr=0.3,0.1

Type RM Length L Ch R = 1,23912,121,121,121
BEGIN DESCRIPTION:
Little Elm Creek A 23911.74
END DESCRIPTION:
XS GIS Cut Line= 3
      1515006.84      6801031.03      1515197.80      6800945.97
      1515458.25      6800876.52
#Sta/Elev= 30
  4779.2 2185.43  4886.7 2180.04  4894.7 2178.58  4900.2 2178.64  4917.9 2173.87
  4923.4 2171.31  4930.4 2170.53  4941.2 2171.35  4944.1 2170.10  4946.6 2169.02
  4963.3 2171.14  4969.9 2166.22  4975.3 2160.70  4984.0 2155.51  4998.0 2154.73
  4998.3 2154.23  5002.0 2154.73  5006.0 2157.95  5016.4 2160.74  5035.3 2161.36
  5047.4 2167.08  5057.8 2170.86  5080.5 2175.14  5099.2 2176.91  5130.2 2177.87
  5150.4 2177.28  5171.6 2175.97  5202.7 2171.92  5230.6 2171.20  5257.8 2172.37
#Mann=4,-1,0
  4779.2    0.07       0  4944.1    0.16       0  4998.0    0.07       0
  5002.0    0.16       0
Bank Sta=4998,5002
Exp/Cntr=0.3,0.1

Type RM Length L Ch R = 1,23791,101,101,101
BEGIN DESCRIPTION:
Little Elm Creek A 23791.34
END DESCRIPTION:
XS GIS Cut Line= 3
      1515086.66      6801109.17      1515291.55      6801029.30
      1515505.11      6800940.75
#Sta/Elev= 30
  4777.3 2180.24  4786.3 2179.07  4793.0 2178.80  4829.2 2178.86  4849.7 2178.21
  4931.6 2175.66  4947.2 2171.44  4957.2 2165.92  4961.4 2163.41  4968.7 2158.05
  4979.4 2153.42  4985.9 2153.76  4991.3 2150.98  4998.0 2150.98  4998.3 2150.48
  5001.8 2150.48  5002.0 2150.98  5015.4 2156.32  5022.6 2160.31  5033.4 2165.22
  5039.3 2169.55  5044.7 2171.68  5063.2 2175.59  5092.5 2174.45  5116.4 2171.14
  5163.3 2168.15  5169.5 2168.17  5174.9 2169.03  5193.4 2168.93  5228.4 2171.82
#Mann=5,-1,0
  4777.3    0.16       0  4849.7    0.07       0  4957.2    0.16       0
  4998.0    0.07       0  5002.0    0.16       0
Bank Sta=4998,5002
Exp/Cntr=0.3,0.1

Type RM Length L Ch R = 1,23690,146,146,146
BEGIN DESCRIPTION:
Little Elm Creek A 23689.93
END DESCRIPTION:
XS GIS Cut Line= 3
      1515168.30      6801246.31      1515336.69      6801116.11
      1515536.36      6800996.31
#Sta/Elev= 30
  4789.5 2176.07  4807.8 2174.80  4835.9 2174.21  4849.4 2174.69  4857.6 2173.81
  4878.4 2174.16  4921.9 2172.38  4928.2 2172.80  4971.7 2165.51  4986.2 2164.89
  4992.5 2163.28  4998.0 2149.44  4998.3 2148.94  5002.0 2149.44  5002.4 2159.42
  5007.3 2155.23  5013.1 2152.36  5022.9 2149.44  5028.7 2149.64  5035.4 2151.39
  5044.2 2155.93  5058.7 2165.94  5071.4 2172.49  5093.7 2173.32  5108.4 2172.00
  5123.9 2168.06  5139.5 2166.53  5197.8 2167.11  5225.0 2170.00  5235.2 2169.88
#Mann=3,-1,0
  4789.5    0.16       0  4998.0    0.07       0  5002.0    0.16       0
Bank Sta=4998,5002
Exp/Cntr=0.3,0.1

Type RM Length L Ch R = 1,23544,98,98,98
BEGIN DESCRIPTION:
Little Elm Creek A 23544.34
END DESCRIPTION:
XS GIS Cut Line= 3
      1515185.89      6801346.56      1515433.26      6801225.05
      1515606.90      6801049.25
#Sta/Elev= 30
  4718.6 2174.47  4747.4 2172.57  4753.0 2173.48  4784.5 2171.93  4842.9 2171.08
  4859.8 2169.48  4873.6 2169.98  4887.9 2169.22  4918.2 2164.92  4940.4 2163.42
  4977.8 2164.15  4985.0 2159.90  4992.4 2153.89  4998.0 2147.48  4998.3 2146.98
  5002.0 2147.48  5014.6 2147.58  5035.8 2160.54  5049.9 2164.91  5064.0 2165.65
  5071.2 2166.90  5078.2 2166.00  5085.3 2166.71  5092.3 2164.39  5134.8 2164.26
  5184.3 2166.56  5198.4 2168.04  5205.5 2167.72  5219.6 2170.15  5241.3 2171.51
#Mann=3,-1,0
  4718.6    0.16       0  4998.0    0.07       0  5002.0    0.16       0
Bank Sta=4998,5002
Exp/Cntr=0.3,0.1

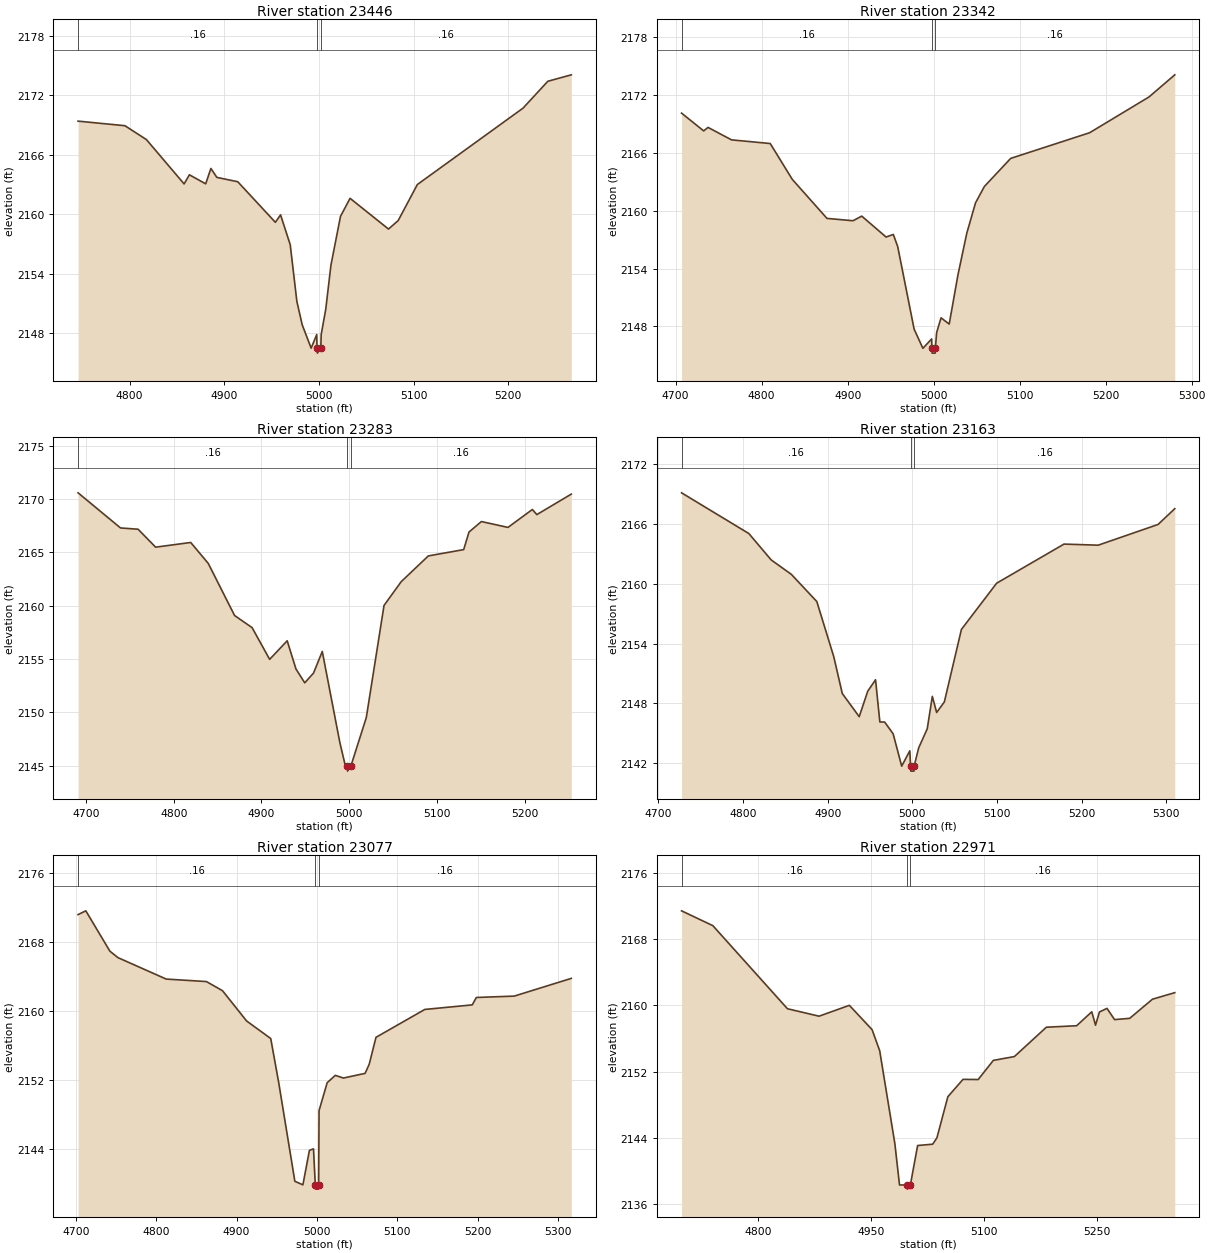
Type RM Length L Ch R = 1,23446,104,104,104
BEGIN DESCRIPTION:
Little Elm Creek A 23445.65
END DESCRIPTION:
XS GIS Cut Line= 3
      1515272.67      6801403.00      1515500.54      6801294.49
      1515765.26      6801248.93
#Sta/Elev= 30
  4745.6 2169.41  4795.1 2168.95  4817.8 2167.55  4857.6 2163.08  4863.2 2164.00
  4880.4 2163.09  4885.9 2164.64  4892.2 2163.74  4914.3 2163.30  4954.0 2159.21
  4959.5 2159.96  4969.7 2156.95  4976.7 2151.24  4982.3 2148.89  4991.8 2146.52
  4997.7 2147.89  4998.0 2146.52  4998.3 2146.02  5002.0 2146.52  5002.4 2147.89
  5007.2 2150.43  5012.7 2154.89  5022.8 2159.81  5032.9 2161.63  5073.5 2158.53
  5083.7 2159.38  5104.0 2163.02  5215.6 2170.72  5241.8 2173.43  5266.6 2174.08
#Mann=3,-1,0
  4745.6    0.16       0  4998.0    0.07       0  5002.0    0.16       0
Bank Sta=4998,5002
Exp/Cntr=0.3,0.1

Type RM Length L Ch R = 1,23342,59,59,59
BEGIN DESCRIPTION:
Little Elm Creek A 23342.03
END DESCRIPTION:
XS GIS Cut Line= 3
      1515257.45      6801426.88      1515496.20      6801394.32
      1515821.94      6801327.44
#Sta/Elev= 30
  4706.9 2170.11  4732.6 2168.27  4737.7 2168.63  4765.0 2167.34  4810.0 2166.96
  4835.6 2163.25  4876.0 2159.20  4906.3 2158.96  4916.4 2159.44  4944.7 2157.27
  4953.1 2157.54  4958.2 2156.29  4977.3 2147.73  4987.5 2145.74  4997.7 2146.71
  4998.0 2145.74  4998.3 2145.24  5001.8 2145.24  5002.0 2145.74  5003.5 2147.37
  5008.6 2148.90  5018.1 2148.25  5028.3 2153.36  5038.5 2157.65  5048.7 2160.81
  5059.0 2162.51  5089.6 2165.42  5181.4 2168.08  5250.3 2171.78  5280.4 2174.08
#Mann=3,-1,0
  4706.9    0.16       0  4998.0    0.07       0  5002.0    0.16       0
Bank Sta=4998,5002
Exp/Cntr=0.3,0.1

Type RM Length L Ch R = 1,23283,120,120,120
BEGIN DESCRIPTION:
Little Elm Creek A 23282.66
END DESCRIPTION:
XS GIS Cut Line= 3
      1515246.61      6801439.89      1515552.62      6801442.06
      1515806.54      6801407.34
#Sta/Elev= 30
  4691.0 2170.57  4739.4 2167.28  4759.4 2167.16  4779.4 2165.48  4819.4 2165.92
  4839.4 2163.96  4869.4 2159.08  4889.4 2157.94  4909.4 2154.97  4929.4 2156.71
  4939.4 2154.07  4949.4 2152.77  4959.4 2153.68  4969.4 2155.71  4989.4 2147.19
  4995.7 2145.00  4998.0 2145.00  4998.2 2144.50  5002.1 2145.00  5019.6 2149.52
  5039.8 2160.02  5059.4 2162.25  5090.3 2164.66  5130.6 2165.25  5136.7 2166.90
  5150.8 2167.88  5181.1 2167.33  5208.9 2169.01  5214.0 2168.53  5253.3 2170.45
#Mann=3,-1,0
  4691.0    0.16       0  4998.0    0.07       0  5002.1    0.16       0
Bank Sta=4998,5002.1
Exp/Cntr=0.3,0.1

Type RM Length L Ch R = 1,23163,86,86,86
BEGIN DESCRIPTION:
Little Elm Creek A 23162.88
END DESCRIPTION:
XS GIS Cut Line= 3
      1515235.74      6801524.52      1515509.22      6801546.23
      1515814.62      6801502.91
#Sta/Elev= 30
  4727.3 2169.14  4806.8 2165.05  4833.2 2162.40  4857.0 2160.95  4887.1 2158.22
  4907.1 2152.69  4917.2 2148.98  4937.2 2146.65  4947.3 2149.21  4956.5 2150.36
  4961.6 2146.12  4967.3 2146.11  4977.3 2144.93  4987.4 2141.68  4997.0 2143.22
  4997.9 2141.68  4998.2 2141.18  5001.9 2141.18  5002.1 2141.68  5007.5 2143.52
  5017.6 2145.43  5023.6 2148.69  5028.7 2147.07  5037.8 2148.13  5058.0 2155.42
  5099.6 2160.06  5179.2 2163.99  5219.6 2163.88  5290.3 2165.96  5310.1 2167.55
#Mann=3,-1,0
  4727.3    0.16       0  4997.9    0.07       0  5002.1    0.16       0
Bank Sta=4997.9,5002.1
Exp/Cntr=0.3,0.1

Type RM Length L Ch R = 1,23077,106,106,106
BEGIN DESCRIPTION:
Little Elm Creek A 23076.6
END DESCRIPTION:
XS GIS Cut Line= 3
      1515205.41      6801633.03      1515496.20      6801633.03
      1515815.26      6801585.28
#Sta/Elev= 30
  4702.9 2171.22  4712.5 2171.66  4742.5 2166.97  4752.5 2166.22  4812.5 2163.73
  4862.5 2163.44  4882.5 2162.38  4912.5 2158.86  4942.5 2156.82  4952.5 2151.65
  4972.5 2140.23  4982.5 2139.82  4990.6 2143.82  4995.7 2144.00  4997.9 2139.82
  4998.2 2139.32  5001.9 2139.32  5002.1 2139.82  5002.6 2148.45  5012.7 2151.69
  5022.8 2152.54  5032.9 2152.23  5059.8 2152.77  5064.9 2153.81  5073.4 2156.96
  5134.1 2160.20  5193.1 2160.73  5198.2 2161.59  5245.3 2161.75  5316.3 2163.81
#Mann=3,-1,0
  4702.9    0.16       0  4997.9    0.07       0  5002.1    0.16       0
Bank Sta=4997.9,5002.1
Exp/Cntr=0.3,0.1

Type RM Length L Ch R = 1,22971,120,120,120
BEGIN DESCRIPTION:
Little Elm Creek A 22971.19
END DESCRIPTION:
XS GIS Cut Line= 3
      1515183.74      6801748.05      1515472.32      6801717.67
      1515834.49      6801682.97
#Sta/Elev= 30
  4698.7 2171.39  4740.2 2169.60  4839.1 2159.58  4881.0 2158.68  4921.2 2159.99
  4951.3 2157.06  4961.4 2154.52  4981.5 2143.32  4987.7 2138.32  4997.9 2138.32
  4998.2 2137.82  5002.1 2138.32  5011.7 2143.08  5031.7 2143.24  5037.3 2144.01
  5051.8 2148.97  5071.9 2151.06  5092.0 2151.04  5112.1 2153.35  5140.0 2153.81
  5182.4 2157.35  5222.6 2157.53  5242.6 2159.21  5247.6 2157.60  5252.8 2159.19
  5262.8 2159.62  5272.8 2158.27  5292.9 2158.42  5323.1 2160.73  5352.7 2161.52
#Mann=3,-1,0
  4698.7    0.16       0  4997.9    0.07       0  5002.1    0.16       0
Bank Sta=4997.9,5002.1
Exp/Cntr=0.3,0.1

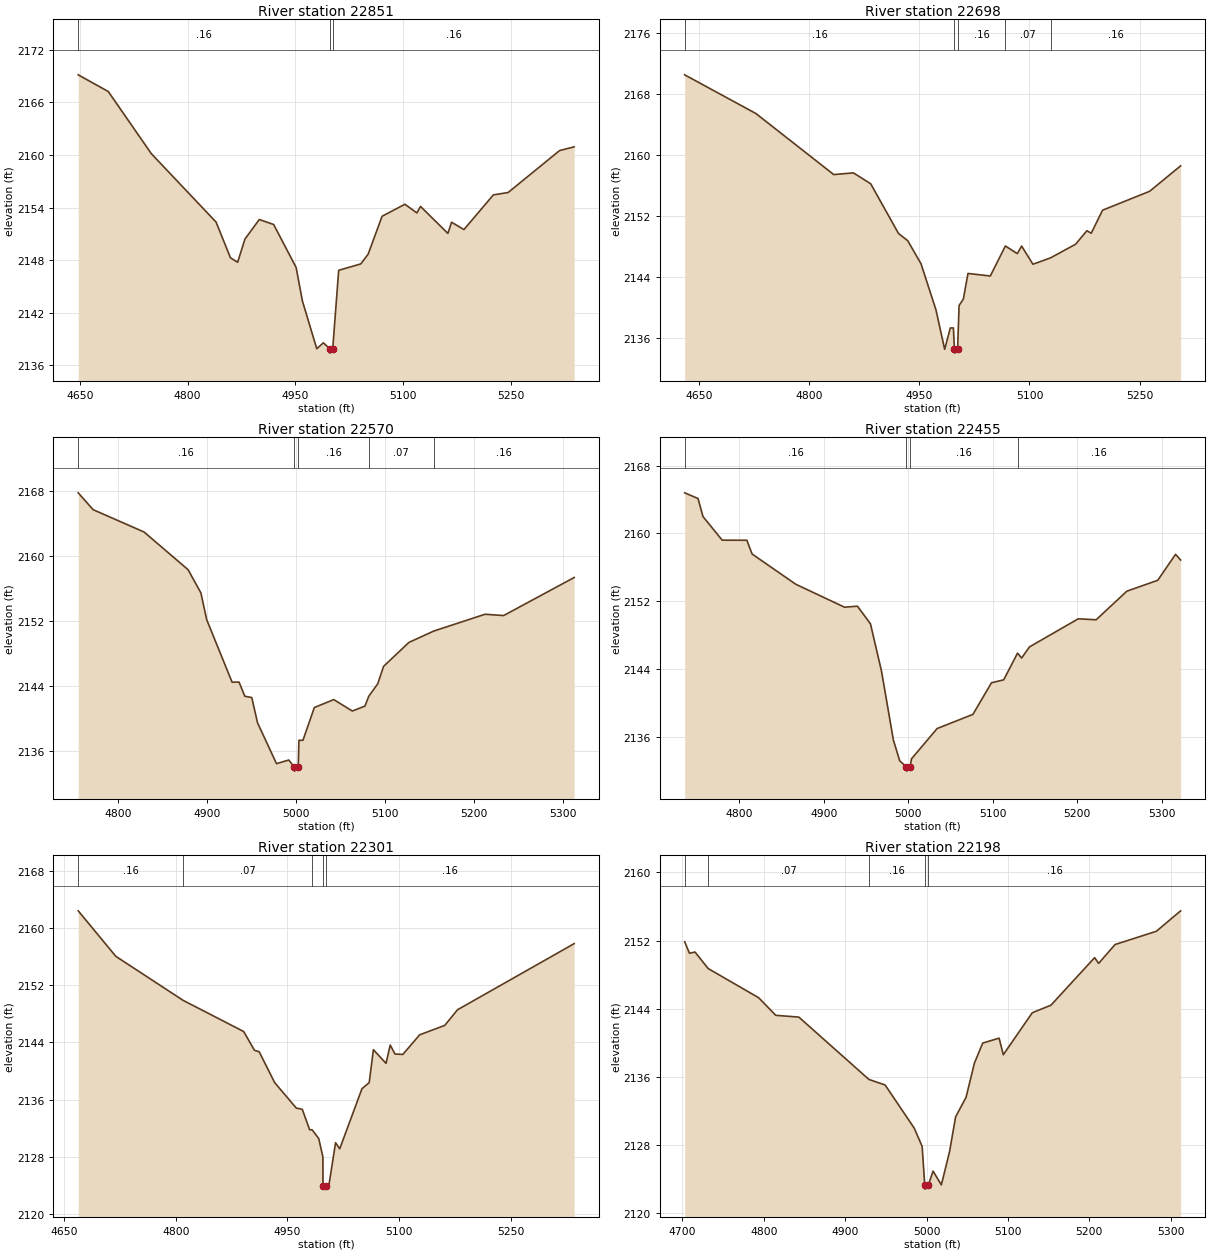
Type RM Length L Ch R = 1,22851,153,153,153
BEGIN DESCRIPTION:
Little Elm Creek A 22850.97
END DESCRIPTION:
XS GIS Cut Line= 3
      1515203.27      6801826.18      1515548.28      6801810.99
      1515884.67      6801735.03
#Sta/Elev= 30
  4647.9 2169.15  4689.7 2167.25  4749.7 2160.15  4839.8 2152.34  4859.8 2148.27
  4869.8 2147.76  4879.9 2150.40  4899.9 2152.64  4919.9 2152.07  4951.2 2147.16
  4959.9 2143.35  4979.9 2137.89  4989.1 2138.57  4997.9 2137.89  4998.2 2137.39
  5002.1 2137.89  5010.4 2146.84  5041.1 2147.57  5051.4 2148.68  5070.8 2153.01
  5102.6 2154.38  5119.2 2153.39  5124.3 2154.13  5162.4 2151.05  5167.5 2152.33
  5184.7 2151.49  5225.7 2155.45  5246.2 2155.72  5317.9 2160.51  5338.1 2160.93
#Mann=3,-1,0
  4647.9    0.16       0  4997.9    0.07       0  5002.1    0.16       0
Bank Sta=4997.9,5002.1
Exp/Cntr=0.3,0.1

Type RM Length L Ch R = 1,22698,128,128,128
BEGIN DESCRIPTION:
Little Elm Creek A 22697.67
END DESCRIPTION:
XS GIS Cut Line= 3
      1515240.09      6802023.67      1515598.19      6801949.87
      1515861.49      6801788.01
#Sta/Elev= 30
  4630.9 2170.48  4727.8 2165.41  4833.7 2157.41  4860.5 2157.63  4884.0 2156.20
  4921.8 2149.69  4934.3 2148.75  4952.4 2145.73  4972.8 2139.67  4984.6 2134.51
  4992.3 2137.31  4996.5 2137.31  4997.9 2134.51  4998.2 2134.01  5002.2 2134.51
  5004.2 2140.25  5010.0 2141.09  5016.3 2144.45  5046.7 2144.12  5067.2 2148.05
  5083.4 2147.05  5089.3 2148.04  5104.7 2145.66  5128.6 2146.49  5162.7 2148.28
  5178.1 2150.05  5184.0 2149.72  5199.4 2152.74  5263.3 2155.21  5305.6 2158.55
#Mann=5,-1,0
  4630.9    0.16       0  4997.9    0.07       0  5002.2    0.16       0
  5067.2    0.07       0  5128.6    0.16       0
Bank Sta=4997.9,5002.2
Exp/Cntr=0.3,0.1

Type RM Length L Ch R = 1,22570,115,115,115
BEGIN DESCRIPTION:
Little Elm Creek A 22570.02
END DESCRIPTION:
XS GIS Cut Line= 3
      1515511.39      6802238.51      1515671.98      6802047.53
      1515873.82      6801815.31
#Sta/Elev= 30
  4755.1 2167.83  4771.9 2165.75  4829.1 2163.00  4878.6 2158.35  4892.9 2155.50
  4899.5 2152.18  4928.0 2144.48  4935.8 2144.50  4942.3 2142.75  4950.1 2142.59
  4956.6 2139.47  4977.9 2134.44  4991.7 2134.89  4997.8 2134.02  4998.1 2133.52
  5002.3 2134.02  5003.1 2137.32  5007.6 2137.32  5020.4 2141.36  5042.2 2142.34
  5063.1 2140.93  5077.3 2141.54  5081.5 2142.74  5091.6 2144.28  5098.2 2146.44
  5126.7 2149.39  5154.6 2150.79  5212.2 2152.86  5233.1 2152.70  5312.3 2157.39
#Mann=5,-1,0
  4755.1    0.16       0  4997.8    0.07       0  5002.3    0.16       0
  5081.5    0.07       0  5154.6    0.16       0
Bank Sta=4997.8,5002.3
Exp/Cntr=0.3,0.1

Type RM Length L Ch R = 1,22455,154,154,154
BEGIN DESCRIPTION:
Little Elm Creek A 22454.97
END DESCRIPTION:
XS GIS Cut Line= 3
      1515611.22      6802355.69      1515747.93      6802136.51
      1515923.69      6801858.77
#Sta/Elev= 30
  4735.4 2164.79  4751.2 2164.12  4757.1 2161.99  4779.8 2159.21  4809.0 2159.20
  4815.2 2157.58  4866.8 2154.02  4924.6 2151.31  4939.9 2151.43  4955.3 2149.35
  4968.4 2143.76  4982.4 2135.67  4989.9 2133.21  4997.8 2132.49  4998.1 2131.99
  5002.3 2132.49  5003.8 2133.43  5034.2 2137.01  5076.6 2138.68  5098.5 2142.40
  5113.0 2142.75  5129.4 2145.90  5134.2 2145.32  5143.5 2146.63  5201.2 2149.94
  5222.4 2149.83  5258.8 2153.20  5295.3 2154.48  5316.4 2157.54  5322.4 2156.87
#Mann=4,-1,0
  4735.4    0.16       0  4997.8    0.07       0  5002.3    0.16       0
  5129.4    0.16       0
Bank Sta=4997.8,5002.3
Exp/Cntr=0.3,0.1

Type RM Length L Ch R = 1,22301,103,103,103
BEGIN DESCRIPTION:
Little Elm Creek A 22301.47
END DESCRIPTION:
XS GIS Cut Line= 3
      1515637.24      6802381.74      1515884.65      6802188.59
      1516037.88      6801871.33
#Sta/Elev= 30
  4669.0 2162.41  4719.5 2156.05  4809.9 2149.89  4891.3 2145.53  4905.8 2142.90
  4912.1 2142.70  4932.9 2138.39  4961.9 2134.83  4970.0 2134.65  4979.9 2131.79
  4983.2 2131.79  4992.1 2130.57  4997.7 2127.98  4997.8 2123.99  4998.1 2123.49
  5002.3 2123.99  5005.7 2123.99  5014.7 2129.98  5020.3 2129.13  5050.2 2137.54
  5059.9 2138.38  5065.5 2142.99  5082.5 2141.08  5088.1 2143.64  5094.6 2142.38
  5105.1 2142.33  5127.7 2145.07  5161.4 2146.39  5178.5 2148.57  5335.2 2157.82
#Mann=5,-1,0
  4669.0    0.16       0  4809.9    0.07       0  4983.2    0.16       0
  4997.8    0.07       0  5002.3    0.16       0
Bank Sta=4997.8,5002.3
Exp/Cntr=0.3,0.1

Type RM Length L Ch R = 1,22198,109,109,109
BEGIN DESCRIPTION:
Little Elm Creek A 22197.78
END DESCRIPTION:
XS GIS Cut Line= 3
      1515784.81      6802436.01      1515982.31      6802221.14
      1516038.73      6801908.64
#Sta/Elev= 30
  4702.8 2151.86  4708.7 2150.51  4715.5 2150.65  4731.7 2148.71  4793.8 2145.28
  4814.7 2143.22  4843.1 2143.01  4929.2 2135.69  4949.1 2135.04  4984.9 2129.97
  4994.6 2127.82  4997.8 2123.31  4998.1 2122.81  5002.3 2123.31  5008.0 2124.93
  5018.2 2123.31  5028.3 2127.22  5035.7 2131.29  5048.6 2133.60  5058.8 2137.60
  5069.0 2139.96  5089.2 2140.54  5094.3 2138.59  5129.9 2143.52  5152.9 2144.41
  5206.5 2149.99  5211.5 2149.32  5231.6 2151.53  5282.4 2153.09  5312.2 2155.49
#Mann=5,-1,0
  4702.8    0.16       0  4731.7    0.07       0  4929.2    0.16       0
  4997.8    0.07       0  5002.3    0.16       0
Bank Sta=4997.8,5002.3
Exp/Cntr=0.3,0.1