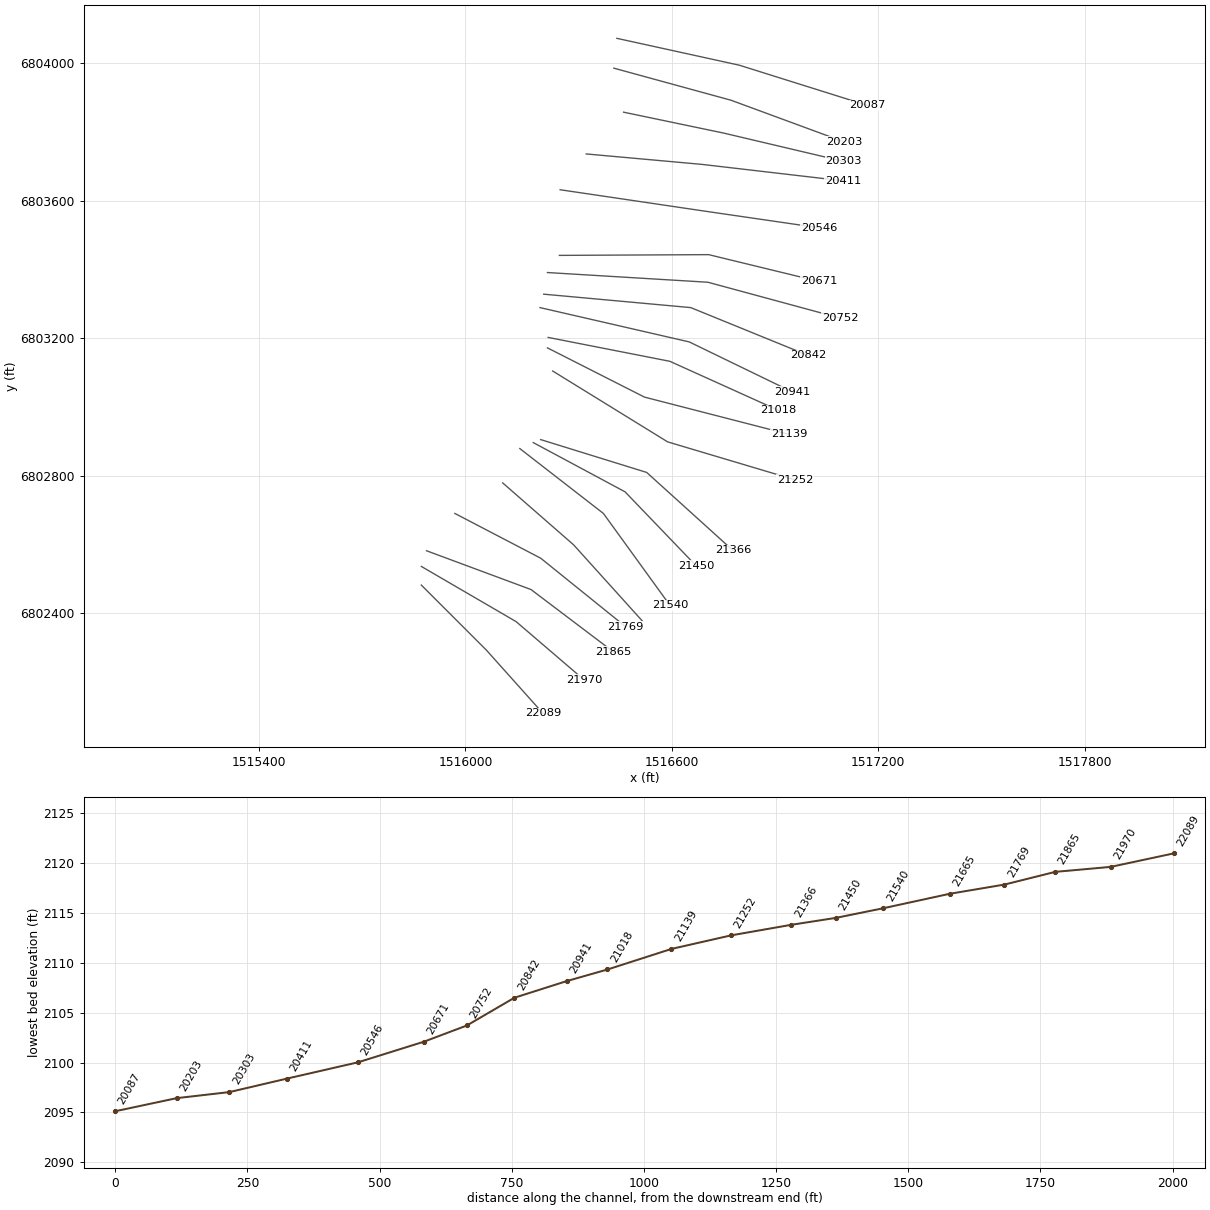
HEC-RAS study Little Elm Creek A.prj: Little Elm Creek A Base Level Engineering

--- Little Elm Creek A.g01 (geometry) --- (continued)

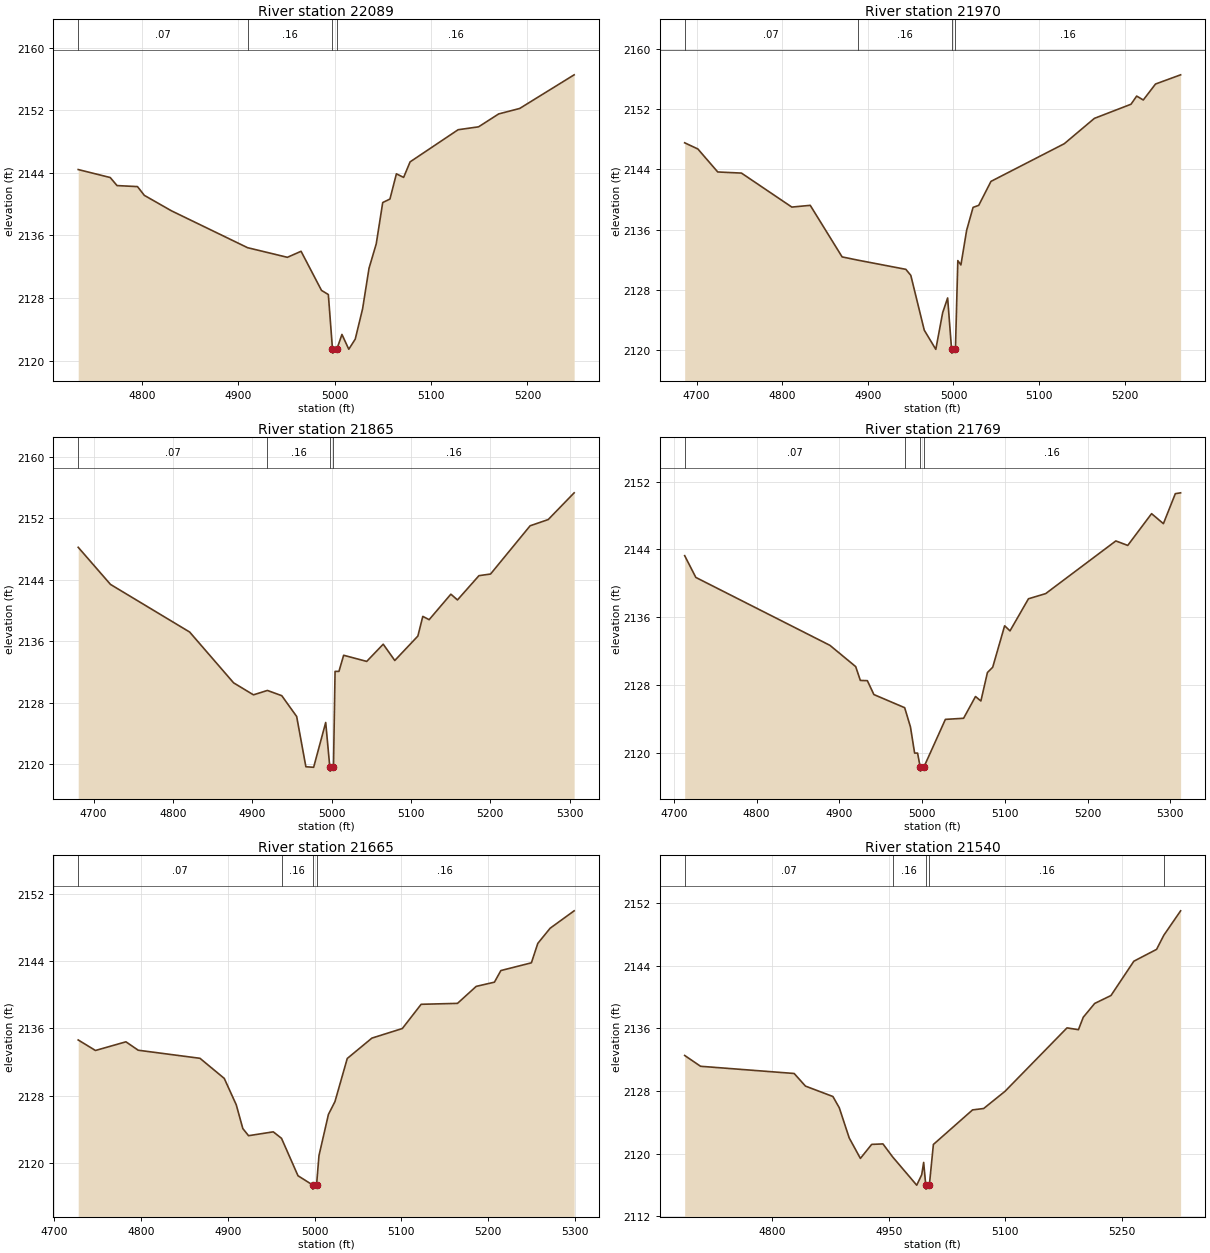
Type RM Length L Ch R = 1,22089,119,119,119
BEGIN DESCRIPTION:
Little Elm Creek A 22088.84
END DESCRIPTION:
XS GIS Cut Line= 3
      1515871.62      6802481.57      1516060.43      6802292.76
      1516225.39      6802108.27
#Sta/Elev= 30
  4734.0 2144.42  4767.2 2143.40  4774.3 2142.37  4795.5 2142.24  4802.6 2141.12
  4830.8 2139.14  4909.7 2134.43  4951.0 2133.20  4965.2 2133.97  4986.4 2128.97
  4993.5 2128.44  4997.8 2121.45  4998.1 2120.95  5002.3 2121.45  5007.6 2123.34
  5014.7 2121.45  5021.4 2122.74  5029.0 2126.60  5035.7 2131.80  5043.2 2134.93
  5049.9 2140.20  5057.4 2140.65  5064.1 2143.87  5071.6 2143.42  5078.3 2145.40
  5128.1 2149.51  5149.3 2149.88  5170.2 2151.53  5192.0 2152.23  5248.5 2156.53
#Mann=4,-1,0
  4734.0    0.07       0  4909.7    0.16       0  4997.8    0.07       0
  5002.3    0.16       0
Bank Sta=4997.8,5002.3
Exp/Cntr=0.3,0.1

Type RM Length L Ch R = 1,21970,105,105,105
BEGIN DESCRIPTION:
Little Elm Creek A 21970.46
END DESCRIPTION:
XS GIS Cut Line= 3
      1515871.66      6802535.80      1516147.24      6802375.22
      1516344.68      6802205.98
#Sta/Elev= 30
  4686.2 2147.51  4701.6 2146.69  4724.8 2143.64  4752.5 2143.49  4811.3 2138.98
  4832.8 2139.21  4870.0 2132.37  4888.3 2131.94  4944.4 2130.72  4950.2 2129.92
  4965.9 2122.65  4979.4 2120.10  4987.4 2124.97  4993.2 2126.92  4997.8 2120.10
  4998.1 2119.60  5002.3 2120.10  5005.1 2131.88  5008.7 2131.30  5015.4 2135.91
  5022.9 2138.94  5029.5 2139.21  5043.8 2142.39  5129.4 2147.39  5164.5 2150.75
  5207.3 2152.63  5213.9 2153.71  5221.6 2153.19  5235.9 2155.31  5265.2 2156.53
#Mann=4,-1,0
  4686.2    0.07       0  4888.3    0.16       0  4997.8    0.07       0
  5002.3    0.16       0
Bank Sta=4997.8,5002.3
Exp/Cntr=0.3,0.1

Type RM Length L Ch R = 1,21865,96,96,96
BEGIN DESCRIPTION:
Little Elm Creek A 21865.16
END DESCRIPTION:
XS GIS Cut Line= 3
      1515886.81      6802581.39      1516190.64      6802468.54
      1516430.73      6802286.85
#Sta/Elev= 30
  4680.5 2148.23  4721.2 2143.40  4821.0 2137.20  4876.4 2130.59  4901.4 2129.03
  4919.0 2129.60  4937.1 2128.92  4955.9 2126.21  4967.5 2119.67  4977.3 2119.60
  4992.5 2125.43  4997.7 2119.60  4998.0 2119.10  5002.3 2119.60  5004.3 2132.08
  5009.2 2132.08  5015.1 2134.18  5044.2 2133.38  5065.0 2135.62  5079.6 2133.50
  5108.7 2136.68  5114.9 2139.24  5122.9 2138.81  5150.3 2142.13  5158.6 2141.38
  5185.7 2144.54  5200.3 2144.75  5250.2 2151.03  5273.0 2151.84  5305.7 2155.32
#Mann=4,-1,0
  4680.5    0.07       0  4919.0    0.16       0  4997.7    0.07       0
  5002.3    0.16       0
Bank Sta=4997.7,5002.3
Exp/Cntr=0.3,0.1

Type RM Length L Ch R = 1,21769,104,104,104
BEGIN DESCRIPTION:
Little Elm Creek A 21769.05
END DESCRIPTION:
XS GIS Cut Line= 3
      1515969.28      6802689.90      1516218.85      6802559.68
      1516466.24      6802360.04
#Sta/Elev= 30
  4713.1 2143.27  4726.6 2140.70  4888.7 2132.68  4919.8 2130.17  4925.4 2128.54
  4933.9 2128.51  4941.8 2126.87  4979.0 2125.32  4986.0 2123.04  4991.0 2119.96
  4994.6 2119.96  4997.7 2118.33  4998.0 2117.83  5002.3 2118.33  5028.2 2123.94
  5050.2 2124.07  5064.6 2126.64  5071.1 2126.11  5079.0 2129.47  5085.4 2130.10
  5099.8 2134.99  5106.3 2134.39  5128.6 2138.18  5149.4 2138.79  5234.2 2145.01
  5248.6 2144.48  5277.4 2148.23  5291.7 2147.05  5306.1 2150.59  5312.5 2150.69
#Mann=4,-1,0
  4713.1    0.07       0  4979.0    0.16       0  4997.7    0.07       0
  5002.3    0.16       0
Bank Sta=4997.7,5002.3
Exp/Cntr=0.3,0.1

Type RM Length L Ch R = 1,21665,125,125,125
BEGIN DESCRIPTION:
Little Elm Creek A 21665.49
END DESCRIPTION:
XS GIS Cut Line= 3
      1516108.21      6802778.84      1516314.34      6802598.75
      1516513.99      6802377.40
#Sta/Elev= 30
  4727.5 2134.63  4747.4 2133.38  4782.5 2134.41  4796.7 2133.41  4867.9 2132.45
  4895.9 2130.06  4909.7 2126.93  4917.3 2124.10  4923.9 2123.25  4952.4 2123.71
  4961.9 2122.94  4980.9 2118.49  4997.7 2117.40  4998.0 2116.90  5002.3 2117.40
  5005.1 2120.89  5016.0 2125.78  5023.5 2127.30  5037.7 2132.43  5066.1 2134.85
  5101.2 2135.99  5122.9 2138.87  5164.8 2138.98  5186.4 2141.00  5207.4 2141.50
  5214.8 2142.88  5250.0 2143.80  5257.4 2146.11  5271.6 2147.91  5299.3 2149.98
#Mann=4,-1,0
  4727.5    0.07       0  4961.9    0.16       0  4997.7    0.07       0
  5002.3    0.16       0
Bank Sta=4997.7,5002.3
Exp/Cntr=0.3,0.1

Type RM Length L Ch R = 1,21540,90,90,90
BEGIN DESCRIPTION:
Little Elm Creek A 21540
END DESCRIPTION:
XS GIS Cut Line= 3
      1516158.05      6802878.72      1516401.14      6802689.89
      1516594.29      6802422.96
#Sta/Elev= 30
  4687.9 2132.52  4708.3 2131.14  4828.6 2130.22  4843.1 2128.61  4878.4 2127.28
  4886.6 2125.84  4899.3 2122.00  4913.7 2119.38  4928.2 2121.17  4942.7 2121.23
  4955.0 2119.59  4986.1 2115.96  4992.5 2117.30  4995.0 2118.87  4997.7 2115.96
  4998.0 2115.46  5002.3 2115.96  5007.5 2121.16  5057.8 2125.57  5072.1 2125.75
  5099.5 2127.94  5179.2 2136.04  5193.9 2135.81  5200.1 2137.40  5214.8 2139.16
  5235.7 2140.17  5265.1 2144.55  5294.3 2146.06  5303.6 2147.86  5325.2 2150.98
#Mann=5,-1,0
  4687.9    0.07       0  4955.0    0.16       0  4997.7    0.07       0
  5002.3    0.16       0  5303.6    0.07       0
Bank Sta=4997.7,5002.3
Exp/Cntr=0.3,0.1

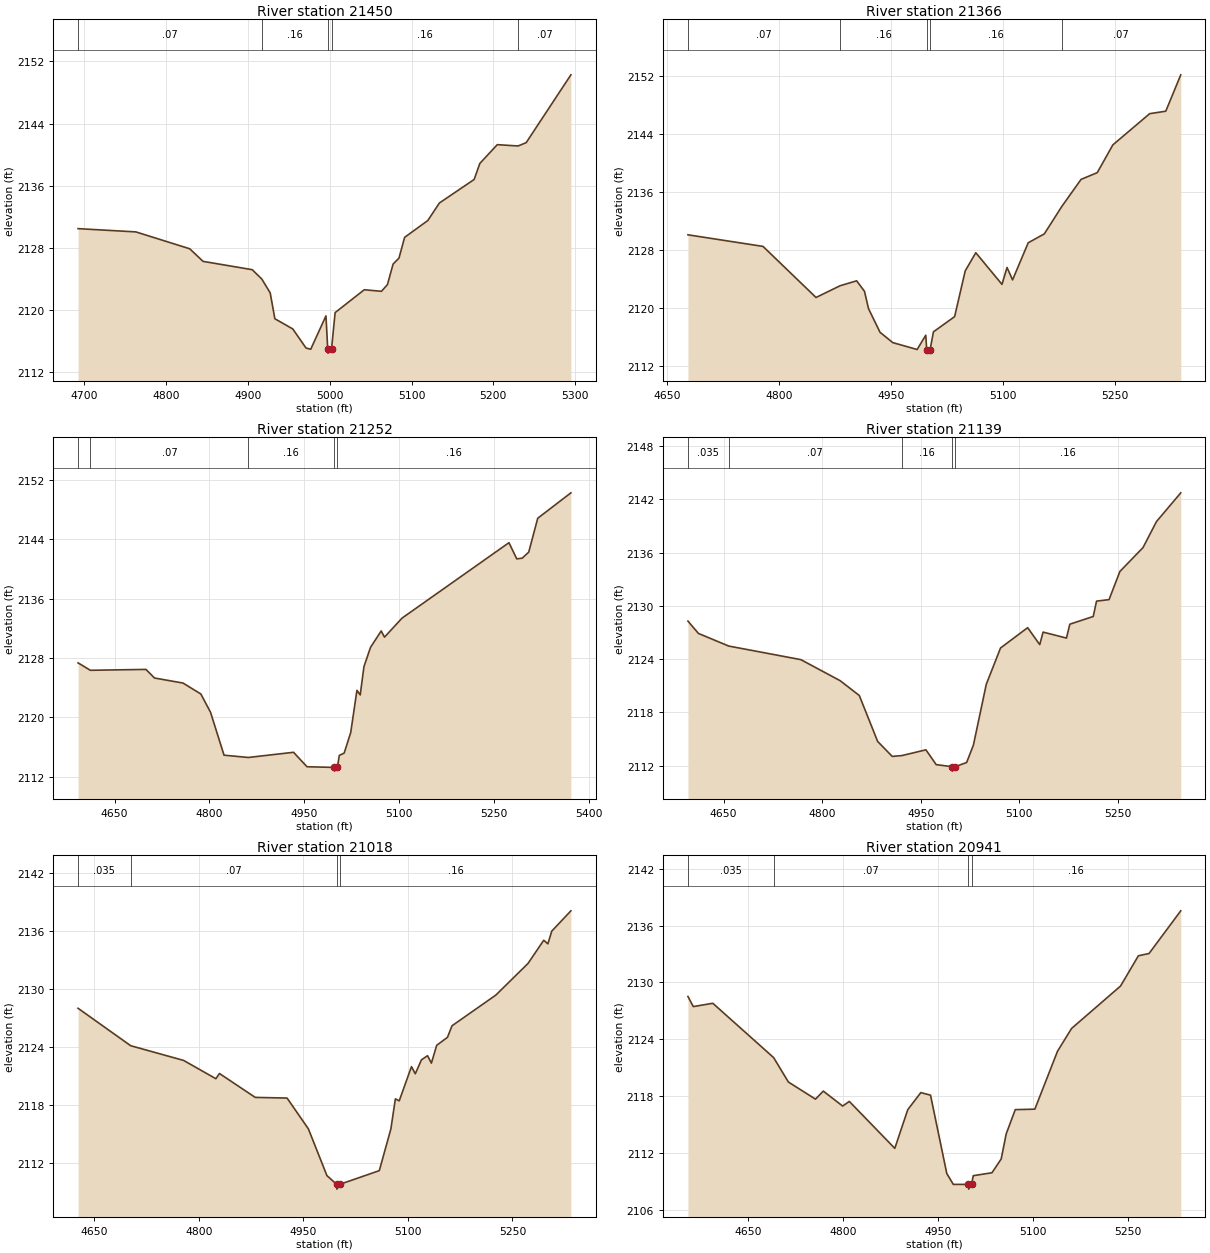
Type RM Length L Ch R = 1,21450,84,84,84
BEGIN DESCRIPTION:
Little Elm Creek A 21450.41
END DESCRIPTION:
XS GIS Cut Line= 3
      1516197.13      6802896.07      1516464.08      6802752.83
      1516671.18      6802537.09
#Sta/Elev= 30
  4692.7 2130.50  4763.3 2130.08  4829.1 2127.91  4845.4 2126.29  4905.5 2125.22
  4917.2 2124.01  4927.4 2122.24  4933.1 2118.91  4955.0 2117.60  4971.2 2115.14
  4976.9 2114.99  4995.5 2119.28  4997.7 2114.99  4998.0 2114.49  5002.3 2114.99
  5006.7 2119.70  5042.3 2122.64  5063.3 2122.44  5070.6 2123.30  5077.5 2125.94
  5084.7 2126.71  5091.6 2129.38  5119.9 2131.54  5134.1 2133.80  5176.5 2136.82
  5183.5 2138.89  5204.8 2141.30  5230.2 2141.13  5240.1 2141.56  5294.7 2150.28
#Mann=5,-1,0
  4692.7    0.07       0  4917.2    0.16       0  4997.7    0.07       0
  5002.3    0.16       0  5230.2    0.07       0
Bank Sta=4997.7,5002.3
Exp/Cntr=0.3,0.1

Type RM Length L Ch R = 1,21366,114,114,114
BEGIN DESCRIPTION:
Little Elm Creek A 21366
END DESCRIPTION:
XS GIS Cut Line= 3
      1516218.81      6802904.75      1516527.01      6802809.25
      1516777.86      6802582.19
#Sta/Elev= 30
  4677.5 2130.13  4778.2 2128.53  4849.3 2121.48  4881.6 2123.10  4903.8 2123.78
  4914.3 2122.33  4919.7 2119.94  4935.2 2116.67  4952.3 2115.25  4984.9 2114.30
  4996.5 2116.27  4997.7 2114.30  4998.0 2113.80  5002.3 2114.30  5006.8 2116.74
  5035.2 2118.84  5049.4 2125.15  5063.6 2127.66  5098.7 2123.29  5105.5 2125.62
  5112.9 2123.91  5133.9 2129.03  5155.5 2130.26  5179.0 2134.05  5204.8 2137.78
  5226.5 2138.71  5247.4 2142.54  5296.8 2146.85  5318.4 2147.19  5338.5 2152.21
#Mann=5,-1,0
  4677.5    0.07       0  4881.6    0.16       0  4997.7    0.07       0
  5002.3    0.16       0  5179.0    0.07       0
Bank Sta=4997.7,5002.3
Exp/Cntr=0.3,0.1

Type RM Length L Ch R = 1,21252,113,113,113
BEGIN DESCRIPTION:
Little Elm Creek A 21251.79
END DESCRIPTION:
XS GIS Cut Line= 3
      1516253.60      6803104.38      1516587.78      6802898.23
      1516958.87      6802787.55
#Sta/Elev= 30
  4592.1 2127.33  4611.6 2126.33  4699.5 2126.45  4713.1 2125.29  4758.2 2124.61
  4786.4 2123.14  4801.8 2120.66  4823.1 2114.89  4861.5 2114.58  4933.1 2115.28
  4954.4 2113.33  4997.7 2113.24  4998.0 2112.74  5002.4 2113.24  5005.5 2114.86
  5013.2 2115.17  5023.6 2117.95  5033.4 2123.63  5038.6 2123.01  5044.5 2126.82
  5054.9 2129.42  5071.8 2131.63  5077.0 2130.80  5104.9 2133.37  5274.0 2143.53
  5286.3 2141.35  5294.9 2141.44  5305.3 2142.26  5319.5 2146.82  5372.0 2150.25
#Mann=5,-1,0
  4592.1   0.035       0  4611.6    0.07       0  4861.5    0.16       0
  4997.7    0.07       0  5002.4    0.16       0
Bank Sta=4997.7,5002.4
Exp/Cntr=0.3,0.1

Type RM Length L Ch R = 1,21139,121,121,121
BEGIN DESCRIPTION:
Little Elm Creek A 21138.88
END DESCRIPTION:
XS GIS Cut Line= 3
      1516238.42      6803171.64      1516520.50      6803028.43
      1516940.72      6802920.13
#Sta/Elev= 30
  4595.6 2128.28  4611.6 2126.89  4657.7 2125.47  4767.5 2123.94  4827.3 2121.57
  4856.5 2119.90  4884.4 2114.73  4906.6 2113.04  4921.3 2113.13  4957.9 2113.78
  4973.6 2112.11  4997.7 2111.88  4998.0 2111.38  5002.4 2111.88  5019.9 2112.35
  5030.2 2114.31  5049.8 2121.16  5071.5 2125.25  5112.8 2127.54  5131.2 2125.63
  5136.3 2127.04  5171.9 2126.37  5177.0 2127.93  5212.6 2128.80  5217.7 2130.53
  5236.7 2130.70  5253.2 2133.87  5288.4 2136.56  5309.0 2139.50  5345.9 2142.73
#Mann=5,-1,0
  4595.6   0.035       0  4657.7    0.07       0  4921.3    0.16       0
  4997.7    0.07       0  5002.4    0.16       0
Bank Sta=4997.7,5002.4
Exp/Cntr=0.3,0.1

Type RM Length L Ch R = 1,21018,77,77,77
BEGIN DESCRIPTION:
Little Elm Creek A 21018.13
END DESCRIPTION:
XS GIS Cut Line= 3
      1516240.53      6803202.05      1516594.29      6803132.60
      1516910.56      6802989.63
#Sta/Elev= 30
  4626.4 2128.01  4702.0 2124.14  4778.0 2122.62  4824.3 2120.73  4829.4 2121.27
  4880.8 2118.80  4926.5 2118.73  4957.1 2115.55  4983.7 2110.72  4997.6 2109.82
  4998.0 2109.32  5002.4 2109.82  5058.9 2111.23  5075.5 2115.53  5082.0 2118.65
  5087.5 2118.44  5105.1 2121.98  5110.6 2121.24  5119.4 2122.68  5128.2 2123.11
  5133.7 2122.34  5141.3 2124.18  5156.8 2125.01  5163.3 2126.20  5226.2 2129.37
  5272.4 2132.64  5295.0 2135.04  5301.0 2134.67  5306.5 2135.98  5334.0 2138.08
#Mann=4,-1,0
  4626.4   0.035       0  4702.0    0.07       0  4997.6    0.07       0
  5002.4    0.16       0
Bank Sta=4997.6,5002.4
Exp/Cntr=0.3,0.1

Type RM Length L Ch R = 1,20941,99,99,99
BEGIN DESCRIPTION:
Little Elm Creek A 20941.31
END DESCRIPTION:
XS GIS Cut Line= 3
      1516216.70      6803288.85      1516650.71      6803189.02
      1516950.06      6803043.69
#Sta/Elev= 30
  4554.7 2128.52  4563.2 2127.45  4594.0 2127.80  4690.0 2122.06  4713.3 2119.48
  4756.1 2117.67  4768.4 2118.52  4799.0 2116.94  4809.5 2117.43  4881.3 2112.47
  4901.8 2116.56  4922.4 2118.36  4937.7 2118.09  4963.4 2109.81  4973.7 2108.66
  4997.6 2108.66  4998.0 2108.16  5002.4 2108.66  5005.2 2109.58  5034.7 2109.89
  5049.3 2111.35  5057.2 2114.00  5071.5 2116.56  5102.4 2116.61  5138.2 2122.73
  5160.4 2125.14  5237.7 2129.62  5265.9 2132.82  5282.7 2133.06  5332.8 2137.57
#Mann=4,-1,0
  4554.7   0.035       0  4690.0    0.07       0  4997.6    0.07       0
  5002.4    0.16       0
Bank Sta=4997.6,5002.4
Exp/Cntr=0.3,0.1

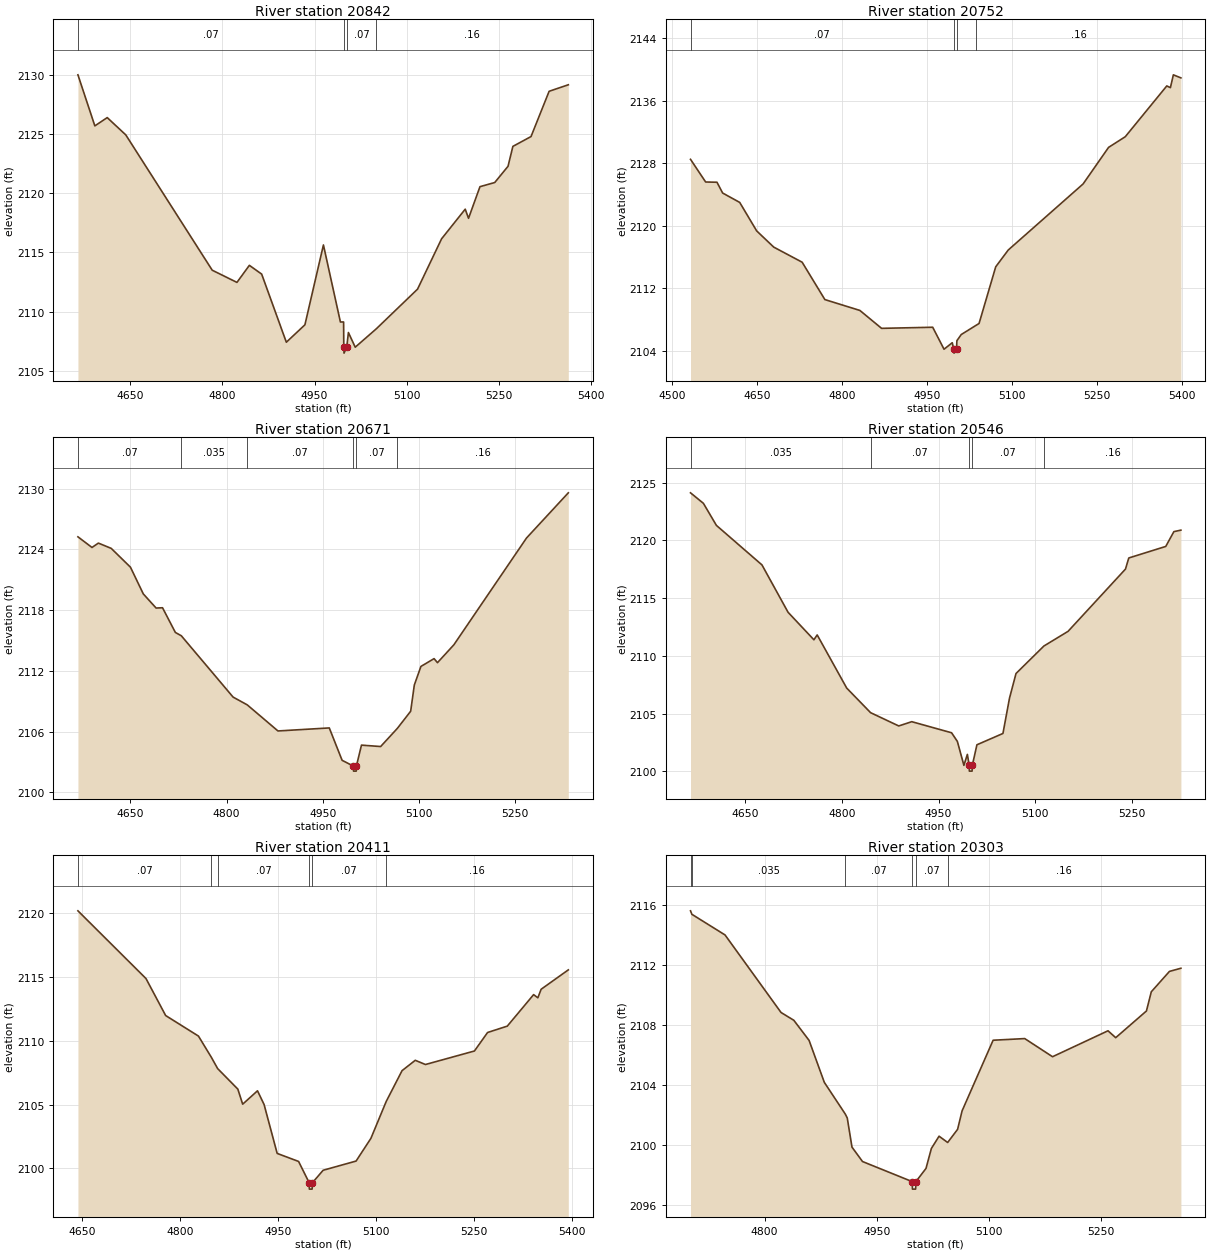
Type RM Length L Ch R = 1,20842,90,90,90
BEGIN DESCRIPTION:
Little Elm Creek A 20842.27
END DESCRIPTION:
XS GIS Cut Line= 3
      1516227.56      6803327.91      1516655.05      6803288.85
      1516995.76      6803149.96
#Sta/Elev= 30
  4565.4 2129.98  4592.9 2125.67  4613.0 2126.37  4643.2 2124.91  4783.7 2113.49
  4823.9 2112.46  4844.1 2113.90  4864.1 2113.16  4904.2 2107.41  4934.4 2108.88
  4964.5 2115.62  4992.1 2109.12  4997.3 2109.12  4997.6 2106.99  4998.0 2106.49
  5002.4 2106.99  5005.1 2108.23  5016.2 2106.99  5050.4 2108.54  5117.5 2111.89
  5156.6 2116.14  5195.0 2118.64  5200.4 2117.87  5219.0 2120.54  5243.0 2120.89
  5264.6 2122.26  5272.5 2123.94  5302.0 2124.77  5331.4 2128.59  5362.6 2129.14
#Mann=4,-1,0
  4565.4    0.07       0  4997.6    0.07       0  5002.4    0.07       0
  5050.4    0.16       0
Bank Sta=4997.6,5002.4
Exp/Cntr=0.3,0.1

Type RM Length L Ch R = 1,20752,81,81,81
BEGIN DESCRIPTION:
Little Elm Creek A 20751.7
END DESCRIPTION:
XS GIS Cut Line= 3
      1516238.37      6803390.85      1516704.96      6803362.64
      1517089.05      6803258.48
#Sta/Elev= 30
  4533.0 2128.50  4559.7 2125.60  4579.7 2125.57  4589.7 2124.19  4619.8 2122.99
  4649.8 2119.34  4679.9 2117.27  4730.0 2115.34  4770.1 2110.56  4831.9 2109.17
  4870.2 2106.88  4960.4 2107.02  4980.4 2104.21  4994.9 2105.04  4997.6 2104.21
  4998.0 2103.71  5002.4 2104.21  5003.1 2105.30  5010.8 2106.09  5036.8 2107.26
  5042.2 2107.50  5071.6 2114.75  5093.7 2116.90  5225.8 2125.35  5270.8 2130.03
  5300.2 2131.39  5373.5 2137.89  5379.9 2137.67  5385.1 2139.31  5398.4 2138.92
#Mann=4,-1,0
  4533.0    0.07       0  4997.6    0.07       0  5002.4    0.07       0
  5036.8    0.16       0
Bank Sta=4997.6,5002.4
Exp/Cntr=0.3,0.1

Type RM Length L Ch R = 1,20671,125,125,125
BEGIN DESCRIPTION:
Little Elm Creek A 20671.44
END DESCRIPTION:
XS GIS Cut Line= 3
      1516273.10      6803440.76      1516707.13      6803442.93
      1517028.33      6803364.80
#Sta/Elev= 30
  4568.2 2125.25  4590.1 2124.20  4600.1 2124.63  4620.1 2124.11  4650.1 2122.25
  4670.1 2119.61  4690.1 2118.21  4700.1 2118.24  4720.1 2115.80  4729.4 2115.47
  4810.1 2109.41  4832.2 2108.64  4880.1 2106.06  4960.1 2106.36  4980.1 2103.16
  4997.6 2102.59  4998.0 2102.09  5002.1 2102.09  5002.4 2102.59  5010.3 2104.66
  5040.2 2104.52  5066.3 2106.32  5087.0 2108.01  5092.7 2110.60  5103.0 2112.44
  5123.5 2113.21  5128.8 2112.81  5154.4 2114.58  5267.6 2125.13  5332.8 2129.60
#Mann=6,-1,0
  4568.2    0.07       0  4729.4   0.035       0  4832.2    0.07       0
  4997.6    0.07       0  5002.4    0.07       0  5066.3    0.16       0
Bank Sta=4997.6,5002.4
Exp/Cntr=0.3,0.1

Type RM Length L Ch R = 1,20546,135,135,135
BEGIN DESCRIPTION:
Little Elm Creek A 20546.27
END DESCRIPTION:
XS GIS Cut Line= 3
      1516275.26      6803631.74      1516700.62      6803568.80
      1517028.27      6803521.06
#Sta/Elev= 30
  4565.1 2124.11  4585.1 2123.20  4605.3 2121.29  4676.0 2117.87  4716.5 2113.77
  4756.6 2111.39  4761.7 2111.81  4807.5 2107.21  4844.6 2105.08  4888.3 2103.93
  4908.5 2104.30  4970.3 2103.34  4979.3 2102.59  4989.4 2100.52  4994.8 2101.47
  4997.6 2100.52  4997.9 2100.02  5002.1 2100.02  5002.5 2100.52  5009.6 2102.30
  5050.0 2103.28  5060.2 2106.34  5070.3 2108.47  5113.6 2110.85  5151.1 2112.12
  5240.2 2117.51  5245.3 2118.47  5302.7 2119.47  5315.3 2120.75  5326.2 2120.88
#Mann=5,-1,0
  4565.1   0.035       0  4844.6    0.07       0  4997.6    0.07       0
  5002.5    0.07       0  5113.6    0.16       0
Bank Sta=4997.6,5002.5
Exp/Cntr=0.3,0.1

Type RM Length L Ch R = 1,20411,108,108,108
BEGIN DESCRIPTION:
Little Elm Creek A 20410.99
END DESCRIPTION:
XS GIS Cut Line= 3
      1516351.20      6803735.90      1516687.60      6803705.52
      1517097.76      6803657.77
#Sta/Elev= 30
  4643.6 2120.20  4747.8 2114.89  4777.9 2111.99  4828.1 2110.38  4847.9 2108.71
  4857.5 2107.83  4888.4 2106.22  4895.8 2105.04  4918.5 2106.09  4928.6 2105.01
  4948.6 2101.18  4981.4 2100.55  4997.6 2098.88  4997.9 2098.38  5002.1 2098.38
  5002.5 2098.88  5019.0 2099.86  5069.4 2100.58  5092.1 2102.36  5115.5 2105.25
  5139.8 2107.67  5160.0 2108.48  5175.6 2108.15  5250.6 2109.21  5270.7 2110.66
  5300.9 2111.16  5341.2 2113.63  5347.7 2113.38  5352.7 2114.05  5394.3 2115.57
#Mann=6,-1,0
  4643.6    0.07       0  4847.9   0.035       0  4857.5    0.07       0
  4997.6    0.07       0  5002.5    0.07       0  5115.5    0.16       0
Bank Sta=4997.6,5002.5
Exp/Cntr=0.3,0.1

Type RM Length L Ch R = 1,20303,100,100,100
BEGIN DESCRIPTION:
Little Elm Creek A 20302.85
END DESCRIPTION:
XS GIS Cut Line= 3
      1516459.77      6803857.42      1516750.54      6803796.66
      1517099.89      6803714.21
#Sta/Elev= 30
  4701.0 2115.60  4702.8 2115.37  4747.2 2113.99  4822.1 2108.82  4839.2 2108.30
  4859.6 2106.96  4880.0 2104.16  4908.0 2102.05  4910.7 2101.78  4917.0 2099.84
  4931.1 2098.88  4997.6 2097.54  4997.9 2097.04  5002.1 2097.04  5002.5 2097.54
  5016.0 2098.42  5023.2 2099.75  5033.5 2100.57  5045.0 2100.15  5058.3 2101.03
  5064.3 2102.26  5105.8 2106.97  5148.1 2107.08  5185.3 2105.87  5259.5 2107.60
  5269.8 2107.14  5310.9 2108.92  5317.4 2110.20  5341.7 2111.56  5357.0 2111.77
#Mann=6,-1,0
  4701.0    0.16       0  4702.8   0.035       0  4908.0    0.07       0
  4997.6    0.07       0  5002.5    0.07       0  5045.0    0.16       0
Bank Sta=4997.6,5002.5
Exp/Cntr=0.3,0.1

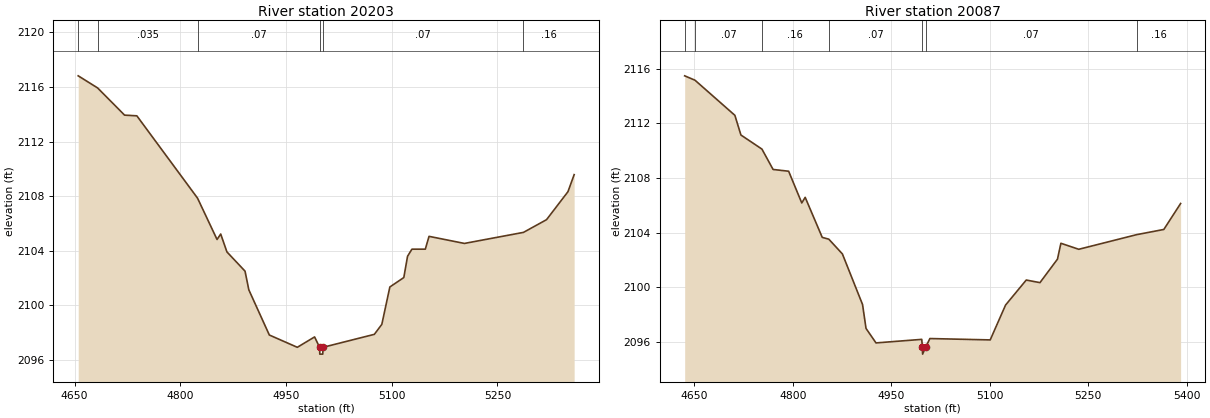
Type RM Length L Ch R = 1,20203,116,116,116
BEGIN DESCRIPTION:
Little Elm Creek A 20202.7
END DESCRIPTION:
XS GIS Cut Line= 3
      1516431.50      6803985.47      1516772.24      6803892.15
      1517101.04      6803771.01
#Sta/Elev= 30
  4655.1 2116.82  4682.7 2115.93  4720.9 2113.94  4738.3 2113.89  4824.4 2107.86
  4852.1 2104.83  4857.3 2105.23  4866.1 2103.92  4891.8 2102.51  4897.2 2101.14
  4926.3 2097.83  4966.0 2096.93  4990.5 2097.69  4997.6 2096.93  4997.9 2096.43
  5002.1 2096.43  5002.5 2096.93  5075.3 2097.88  5085.9 2098.61  5097.3 2101.35
  5117.1 2102.04  5122.4 2103.60  5128.6 2104.12  5147.6 2104.12  5152.9 2105.06
  5203.1 2104.54  5286.9 2105.35  5319.6 2106.28  5350.0 2108.33  5358.8 2109.58
#Mann=6,-1,0
  4655.1    0.16       0  4682.7   0.035       0  4824.4    0.07       0
  4997.6    0.07       0  5002.5    0.07       0  5286.9    0.16       0
Bank Sta=4997.6,5002.5
Exp/Cntr=0.3,0.1

Type RM Length L Ch R = 1,20087,114,114,114
BEGIN DESCRIPTION:
Little Elm Creek A 20087.18
END DESCRIPTION:
XS GIS Cut Line= 3
      1516440.25      6804072.26      1516796.11      6803994.15
      1517169.42      6803876.94
#Sta/Elev= 30
  4635.4 2115.48  4651.1 2115.16  4711.9 2112.59  4721.1 2111.15  4753.1 2110.12
  4770.1 2108.63  4793.8 2108.50  4813.8 2106.18  4819.0 2106.59  4845.0 2103.66
  4855.0 2103.53  4875.7 2102.45  4906.4 2098.75  4911.7 2097.00  4926.9 2095.94
  4996.6 2096.20  4997.6 2095.62  4997.9 2095.12  5002.5 2095.62  5009.0 2096.26
  5100.9 2096.16  5124.3 2098.71  5155.8 2100.54  5176.7 2100.35  5203.4 2102.07
  5208.6 2103.23  5235.8 2102.79  5324.0 2103.86  5365.4 2104.24  5391.0 2106.14
#Mann=7,-1,0
  4635.4    0.16       0  4651.1    0.07       0  4753.1    0.16       0
  4855.0    0.07       0  4997.6    0.07       0  5002.5    0.07       0
  5324.0    0.16       0
Bank Sta=4997.6,5002.5
Exp/Cntr=0.3,0.1