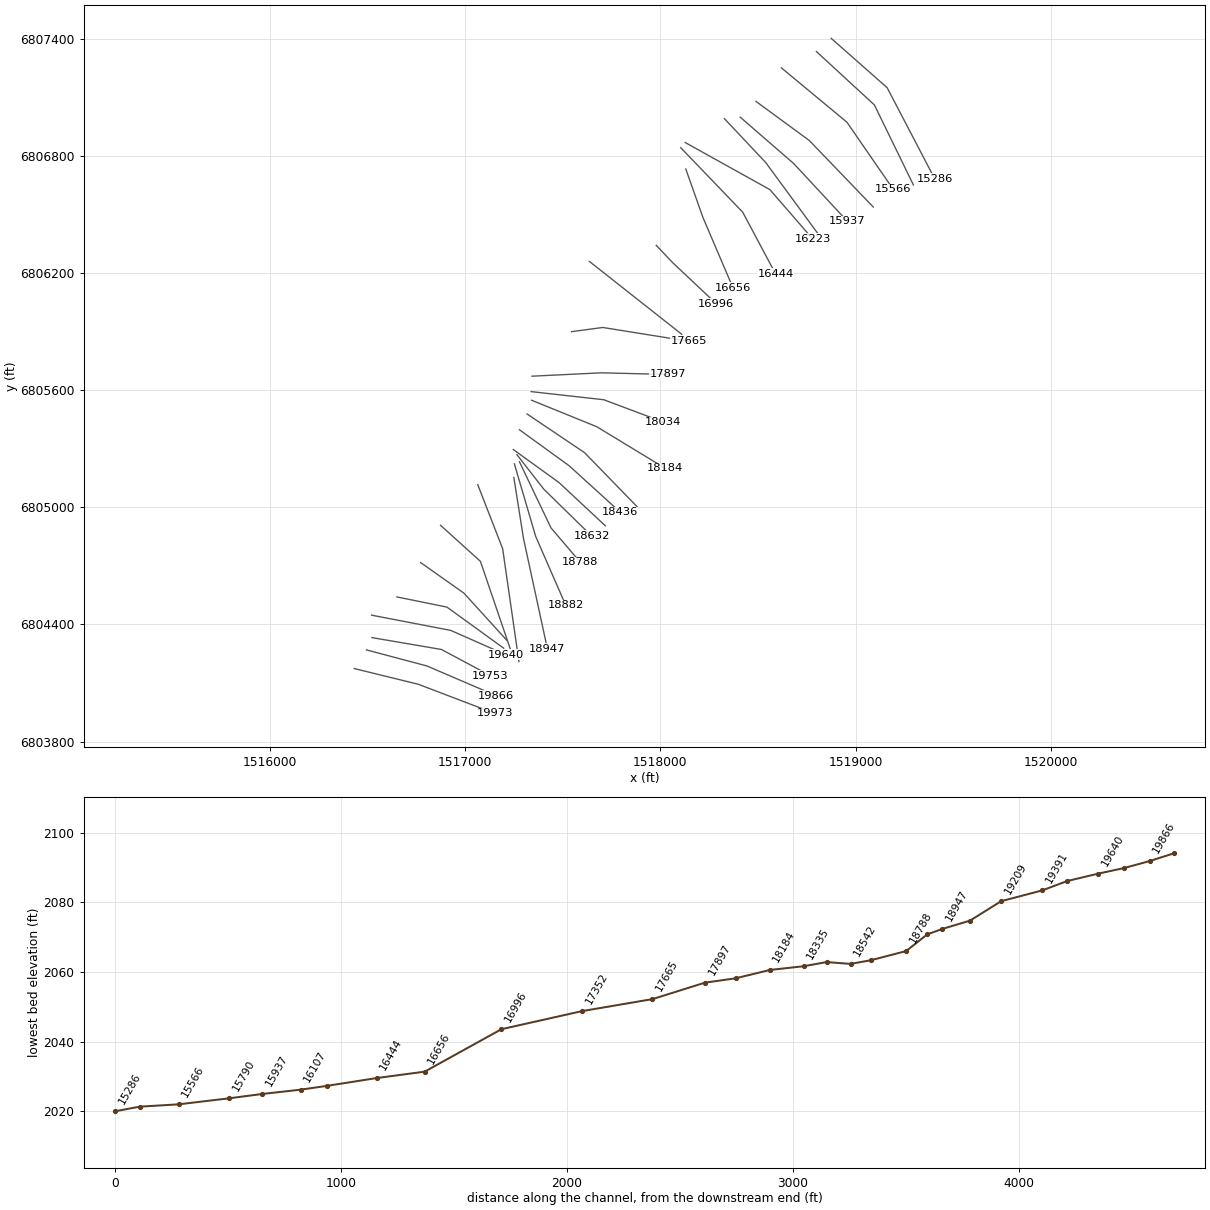
HEC-RAS study Little Elm Creek A.prj: Little Elm Creek A Base Level Engineering

--- Little Elm Creek A.g01 (geometry) --- (continued)

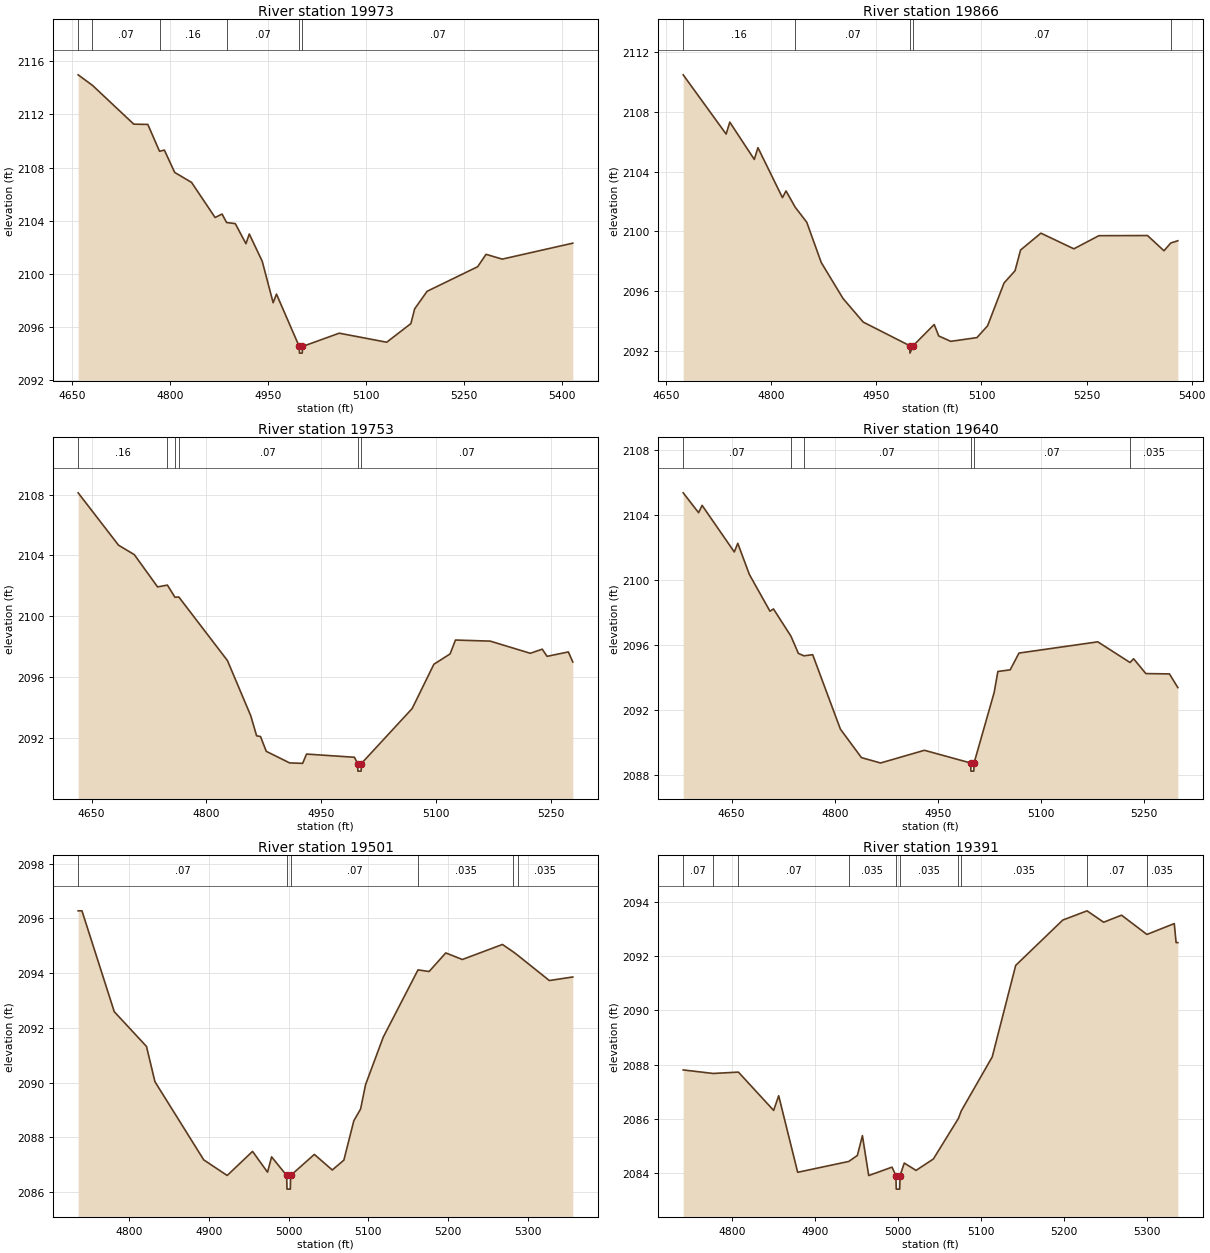
Type RM Length L Ch R = 1,19973,107,107,107
BEGIN DESCRIPTION:
Little Elm Creek A 19973
END DESCRIPTION:
XS GIS Cut Line= 3
      1516431.50      6804174.27      1516759.22      6804093.97
      1517151.00      6803944.62
#Sta/Elev= 30
  4659.3 2114.97  4681.2 2114.18  4744.4 2111.26  4765.9 2111.24  4783.8 2109.22
  4791.2 2109.31  4807.0 2107.63  4832.8 2106.88  4868.8 2104.24  4879.5 2104.50
  4886.4 2103.86  4899.7 2103.78  4916.0 2102.27  4921.1 2103.00  4940.9 2100.95
  4957.6 2097.83  4962.7 2098.48  4997.5 2094.54  4997.9 2094.04  5002.1 2094.04
  5002.5 2094.54  5058.7 2095.54  5131.3 2094.86  5168.3 2096.26  5174.1 2097.37
  5193.1 2098.69  5270.5 2100.54  5283.3 2101.47  5308.1 2101.11  5416.0 2102.31
#Mann=6,-1,0
  4659.3    0.16       0  4681.2    0.07       0  4783.8    0.16       0
  4886.4    0.07       0  4997.5    0.07       0  5002.5    0.07       0
Bank Sta=4997.5,5002.5
Exp/Cntr=0.3,0.1

Type RM Length L Ch R = 1,19866,113,113,113
BEGIN DESCRIPTION:
Little Elm Creek A 19865.68
END DESCRIPTION:
XS GIS Cut Line= 3
      1516494.47      6804269.75      1516804.79      6804187.29
      1517158.56      6804035.36
#Sta/Elev= 30
  4674.2 2110.48  4735.5 2106.51  4740.7 2107.31  4775.7 2104.81  4780.9 2105.60
  4815.9 2102.25  4821.0 2102.70  4834.1 2101.61  4850.6 2100.60  4871.3 2097.90
  4902.4 2095.49  4931.2 2093.91  4997.5 2092.33  4997.9 2091.83  5002.5 2092.33
  5032.5 2093.75  5039.0 2092.98  5056.1 2092.62  5093.5 2092.87  5108.7 2093.66
  5132.2 2096.53  5147.9 2097.35  5155.8 2098.74  5184.8 2099.87  5231.9 2098.82
  5267.6 2099.70  5337.0 2099.71  5360.5 2098.69  5370.2 2099.21  5380.3 2099.36
#Mann=5,-1,0
  4674.2    0.16       0  4834.1    0.07       0  4997.5    0.07       0
  5002.5    0.07       0  5370.2   0.035       0
Bank Sta=4997.5,5002.5
Exp/Cntr=0.3,0.1

Type RM Length L Ch R = 1,19753,113,113,113
BEGIN DESCRIPTION:
Little Elm Creek A 19752.9
END DESCRIPTION:
XS GIS Cut Line= 3
      1516522.69      6804332.68      1516878.57      6804271.92
      1517130.16      6804137.46
#Sta/Elev= 30
  4632.4 2108.11  4685.2 2104.67  4705.8 2104.05  4736.2 2101.93  4749.0 2102.05
  4758.9 2101.25  4763.9 2101.27  4827.5 2097.09  4857.9 2093.47  4865.6 2092.15
  4870.7 2092.10  4878.2 2091.13  4908.7 2090.37  4925.7 2090.34  4930.8 2090.95
  4993.4 2090.74  4997.5 2090.33  4997.9 2089.83  5002.1 2089.83  5002.5 2090.33
  5068.8 2093.94  5097.2 2096.85  5118.4 2097.53  5125.4 2098.44  5170.8 2098.37
  5223.2 2097.57  5238.8 2097.84  5245.1 2097.37  5272.9 2097.66  5278.7 2097.00
#Mann=6,-1,0
  4632.4    0.16       0  4749.0    0.07       0  4758.9    0.16       0
  4763.9    0.07       0  4997.5    0.07       0  5002.5    0.07       0
Bank Sta=4997.5,5002.5
Exp/Cntr=0.3,0.1

Type RM Length L Ch R = 1,19640,139,139,139
BEGIN DESCRIPTION:
Little Elm Creek A 19640.22
END DESCRIPTION:
XS GIS Cut Line= 3
      1516520.51      6804447.70      1516926.32      6804369.58
      1517206.25      6804245.89
#Sta/Elev= 30
  4579.5 2105.34  4601.9 2104.12  4607.0 2104.57  4653.8 2101.71  4658.9 2102.24
  4675.7 2100.33  4705.7 2098.07  4710.8 2098.21  4736.3 2096.53  4747.0 2095.48
  4755.0 2095.33  4767.8 2095.40  4808.1 2090.83  4838.7 2089.08  4866.5 2088.75
  4930.3 2089.53  4997.5 2088.75  4997.9 2088.25  5002.1 2088.25  5002.5 2088.75
  5031.7 2093.08  5037.1 2094.37  5055.0 2094.47  5067.8 2095.50  5182.4 2096.19
  5229.3 2094.92  5234.5 2095.15  5252.3 2094.24  5286.6 2094.22  5298.8 2093.38
#Mann=6,-1,0
  4579.5    0.07       0  4736.3    0.16       0  4755.0    0.07       0
  4997.5    0.07       0  5002.5    0.07       0  5229.3   0.035       0
Bank Sta=4997.5,5002.5
Exp/Cntr=0.3,0.1

Type RM Length L Ch R = 1,19501,110,110,110
BEGIN DESCRIPTION:
Little Elm Creek A 19500.71
END DESCRIPTION:
XS GIS Cut Line= 3
      1516650.68      6804541.03      1516906.79      6804488.94
      1517197.55      6804278.46
#Sta/Elev= 30
  4736.0 2096.28  4740.8 2096.28  4781.3 2092.59  4821.7 2091.32  4832.3 2090.03
  4893.5 2087.17  4922.9 2086.60  4954.7 2087.48  4973.5 2086.72  4978.6 2087.28
  4997.5 2086.60  4997.9 2086.10  5002.1 2086.10  5002.5 2086.60  5032.2 2087.37
  5054.7 2086.80  5069.2 2087.16  5081.7 2088.60  5090.2 2089.03  5096.4 2089.92
  5118.6 2091.66  5162.2 2094.12  5176.1 2094.06  5197.0 2094.74  5217.8 2094.50
  5268.1 2095.05  5281.6 2094.78  5287.0 2094.66  5326.9 2093.73  5356.3 2093.86
#Mann=6,-1,0
  4736.0    0.07       0  4997.5    0.07       0  5002.5    0.07       0
  5162.2   0.035       0  5281.6    0.07       0  5287.0   0.035       0
Bank Sta=4997.5,5002.5
Exp/Cntr=0.3,0.1

Type RM Length L Ch R = 1,19391,182,182,182
BEGIN DESCRIPTION:
Little Elm Creek A 19390.87
END DESCRIPTION:
XS GIS Cut Line= 3
      1516772.20      6804716.83      1516993.59      6804560.55
      1517212.79      6804319.65
#Sta/Elev= 30
  4740.9 2087.81  4777.1 2087.68  4807.5 2087.73  4850.0 2086.32  4856.1 2086.86
  4879.0 2084.04  4940.7 2084.44  4951.0 2084.66  4957.1 2085.39  4964.7 2083.92
  4992.8 2084.23  4997.5 2083.92  4997.9 2083.42  5002.1 2083.42  5002.5 2083.92
  5007.6 2084.38  5021.8 2084.11  5042.7 2084.53  5073.0 2086.03  5076.3 2086.30
  5113.7 2088.29  5142.0 2091.66  5198.8 2093.33  5228.1 2093.67  5248.1 2093.25
  5269.7 2093.51  5300.3 2092.80  5333.3 2093.20  5335.5 2092.50  5337.6 2092.50
#Mann=10,-1,0
  4740.9    0.07       0  4777.1   0.035       0  4807.5    0.07       0
  4940.7   0.035       0  4997.5   0.035       0  5002.5   0.035       0
  5073.0    0.07       0  5076.3   0.035       0  5228.1    0.07       0
  5300.3   0.035       0
Bank Sta=4997.5,5002.5
Exp/Cntr=0.3,0.1

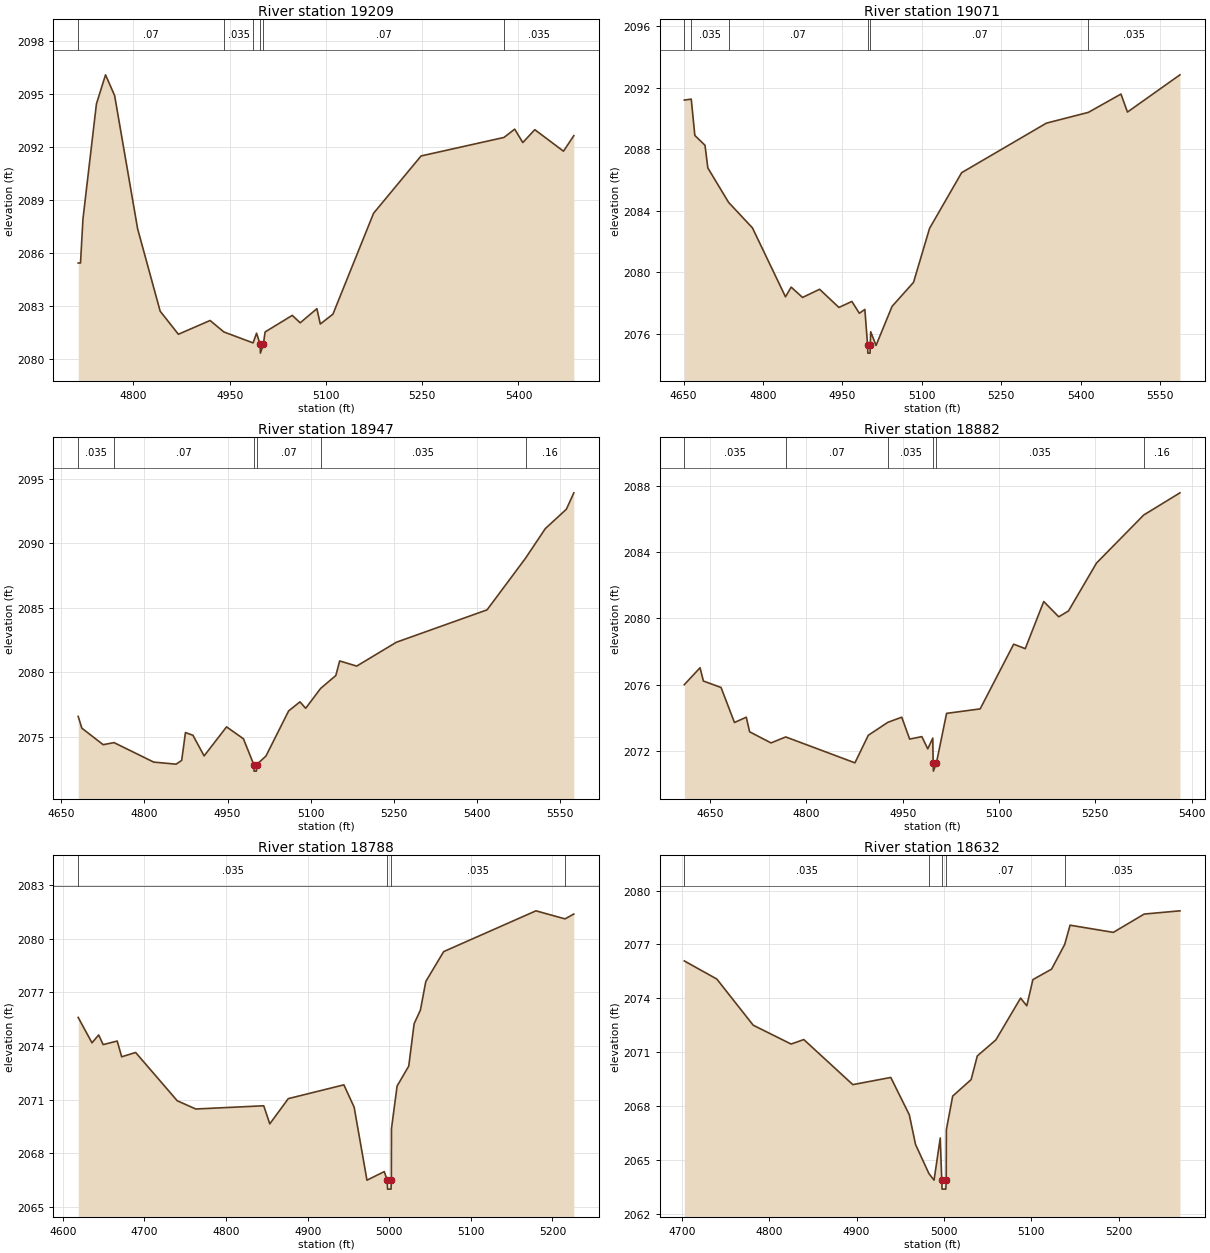
Type RM Length L Ch R = 1,19209,138,138,138
BEGIN DESCRIPTION:
Little Elm Creek A 19209.39
END DESCRIPTION:
XS GIS Cut Line= 3
      1516874.24      6804907.77      1517078.23      6804723.31
      1517238.70      6804252.74
#Sta/Elev= 30
  4714.0 2085.43  4717.6 2085.43  4721.4 2087.92  4742.4 2094.45  4756.6 2096.10
  4770.8 2094.92  4806.6 2087.37  4841.7 2082.70  4870.1 2081.39  4919.5 2082.17
  4941.0 2081.52  4986.5 2080.90  4991.9 2081.45  4997.5 2080.82  4997.9 2080.32
  5002.5 2080.82  5005.2 2081.52  5047.5 2082.46  5059.9 2082.04  5085.9 2082.84
  5091.2 2081.97  5110.9 2082.53  5174.2 2088.25  5248.2 2091.50  5377.4 2092.55
  5394.1 2093.02  5406.7 2092.26  5425.4 2092.99  5470.1 2091.77  5486.2 2092.65
#Mann=6,-1,0
  4714.0    0.07       0  4941.0   0.035       0  4986.5    0.07       0
  4997.5    0.07       0  5002.5    0.07       0  5377.4   0.035       0
Bank Sta=4997.5,5002.5
Exp/Cntr=0.3,0.1

Type RM Length L Ch R = 1,19071,124,124,124
BEGIN DESCRIPTION:
Little Elm Creek A 19070.78
END DESCRIPTION:
XS GIS Cut Line= 3
      1517064.56      6805116.09      1517192.16      6804787.98
      1517275.49      6804209.91
#Sta/Elev= 30
  4651.3 2091.19  4664.4 2091.25  4671.2 2088.89  4690.4 2088.25  4695.7 2086.78
  4734.9 2084.54  4780.0 2082.88  4842.4 2078.40  4853.1 2079.03  4874.6 2078.36
  4906.8 2078.89  4943.3 2077.71  4967.8 2078.10  4981.9 2077.33  4992.3 2077.58
  4997.5 2075.24  4997.9 2074.74  5002.1 2074.74  5002.5 2075.24  5003.3 2076.13
  5013.4 2075.24  5043.7 2077.78  5084.2 2079.34  5114.5 2082.85  5175.1 2086.47
  5335.2 2089.69  5414.5 2090.39  5476.0 2091.58  5488.3 2090.41  5587.4 2092.83
#Mann=6,-1,0
  4651.3    0.07       0  4664.4   0.035       0  4734.9    0.07       0
  4997.5    0.07       0  5002.5    0.07       0  5414.5   0.035       0
Bank Sta=4997.5,5002.5
Exp/Cntr=0.3,0.1

Type RM Length L Ch R = 1,18947,65,65,65
BEGIN DESCRIPTION:
Little Elm Creek A 18947.36
END DESCRIPTION:
XS GIS Cut Line= 3
      1517249.46      6805152.54      1517298.93      6804840.07
      1517421.33      6804274.94
#Sta/Elev= 30
  4680.5 2076.57  4687.1 2075.66  4725.6 2074.38  4745.2 2074.54  4816.8 2073.03
  4857.2 2072.87  4867.3 2073.16  4874.1 2075.32  4887.6 2075.11  4907.8 2073.51
  4948.3 2075.76  4978.7 2074.84  4997.5 2072.83  4997.9 2072.33  5002.2 2072.33
  5002.5 2072.83  5019.4 2073.50  5060.4 2077.00  5080.8 2077.70  5091.1 2077.20
  5118.1 2078.74  5145.5 2079.74  5152.5 2080.87  5183.2 2080.47  5254.8 2082.32
  5418.5 2084.83  5487.9 2088.83  5523.7 2091.13  5561.7 2092.63  5575.1 2093.90
#Mann=6,-1,0
  4680.5   0.035       0  4745.2    0.07       0  4997.5    0.07       0
  5002.5    0.07       0  5118.1   0.035       0  5487.9    0.16       0
Bank Sta=4997.5,5002.5
Exp/Cntr=0.3,0.1

Type RM Length L Ch R = 1,18882,94,94,94
BEGIN DESCRIPTION:
Little Elm Creek A 18881.97
END DESCRIPTION:
XS GIS Cut Line= 3
      1517252.05      6805222.91      1517361.43      6804850.48
      1517515.06      6804498.95
#Sta/Elev= 30
  4610.0 2076.01  4634.5 2077.03  4639.7 2076.23  4667.2 2075.84  4688.1 2073.73
  4706.5 2074.05  4711.7 2073.17  4745.0 2072.50  4767.9 2072.86  4875.7 2071.30
  4896.5 2072.96  4926.9 2073.74  4948.6 2074.05  4960.9 2072.73  4979.9 2072.88
  4989.1 2072.14  4996.9 2072.79  4997.5 2071.30  4997.9 2070.80  5002.6 2071.30
  5018.4 2074.28  5070.7 2074.55  5122.9 2078.45  5140.9 2078.18  5169.7 2081.02
  5193.1 2080.10  5208.2 2080.45  5251.9 2083.34  5325.3 2086.23  5381.8 2087.57
#Mann=6,-1,0
  4610.0   0.035       0  4767.9    0.07       0  4926.9   0.035       0
  4997.5   0.035       0  5002.6   0.035       0  5325.3    0.16       0
Bank Sta=4997.5,5002.6
Exp/Cntr=0.3,0.1

Type RM Length L Ch R = 1,18788,156,156,156
BEGIN DESCRIPTION:
Little Elm Creek A 18788.16
END DESCRIPTION:
XS GIS Cut Line= 3
      1517278.10      6805233.29      1517439.56      6804894.75
      1517590.33      6804717.98
#Sta/Elev= 30
  4618.8 2075.60  4635.7 2074.18  4643.9 2074.62  4649.4 2074.08  4666.6 2074.28
  4672.1 2073.40  4689.2 2073.64  4740.2 2070.94  4762.9 2070.48  4846.2 2070.66
  4853.6 2069.65  4876.3 2071.06  4944.4 2071.83  4957.0 2070.58  4972.7 2066.50
  4993.9 2066.98  4997.5 2066.50  4997.9 2066.00  5002.2 2066.00  5002.6 2066.50
  5002.7 2069.37  5009.6 2071.76  5023.9 2072.88  5030.5 2075.25  5038.2 2076.01
  5044.8 2077.61  5066.7 2079.28  5179.8 2081.56  5215.4 2081.11  5226.2 2081.38
#Mann=4,-1,0
  4618.8   0.035       0  4997.5   0.035       0  5002.6   0.035       0
  5215.4    0.16       0
Bank Sta=4997.5,5002.6
Exp/Cntr=0.3,0.1

Type RM Length L Ch R = 1,18632,90,90,90
BEGIN DESCRIPTION:
Little Elm Creek A 18631.78
END DESCRIPTION:
XS GIS Cut Line= 3
      1517265.09      6805269.73      1517403.10      6805092.67
      1517647.88      6804853.10
#Sta/Elev= 30
  4703.0 2076.08  4740.2 2075.07  4781.8 2072.50  4825.2 2071.45  4839.7 2071.70
  4895.8 2069.19  4939.2 2069.59  4960.4 2067.51  4967.5 2065.86  4982.8 2064.24
  4988.7 2063.87  4995.8 2066.22  4997.5 2063.87  4997.9 2063.37  5002.2 2063.37
  5002.6 2063.87  5002.8 2066.68  5010.0 2068.55  5031.1 2069.47  5038.2 2070.79
  5059.4 2071.68  5087.7 2074.01  5094.8 2073.58  5101.8 2075.04  5123.1 2075.62
  5138.1 2076.99  5144.3 2078.07  5193.8 2077.67  5229.1 2078.69  5270.0 2078.87
#Mann=5,-1,0
  4703.0   0.035       0  4982.8    0.07       0  4997.5    0.07       0
  5002.6    0.07       0  5138.1   0.035       0
Bank Sta=4997.5,5002.6
Exp/Cntr=0.3,0.1

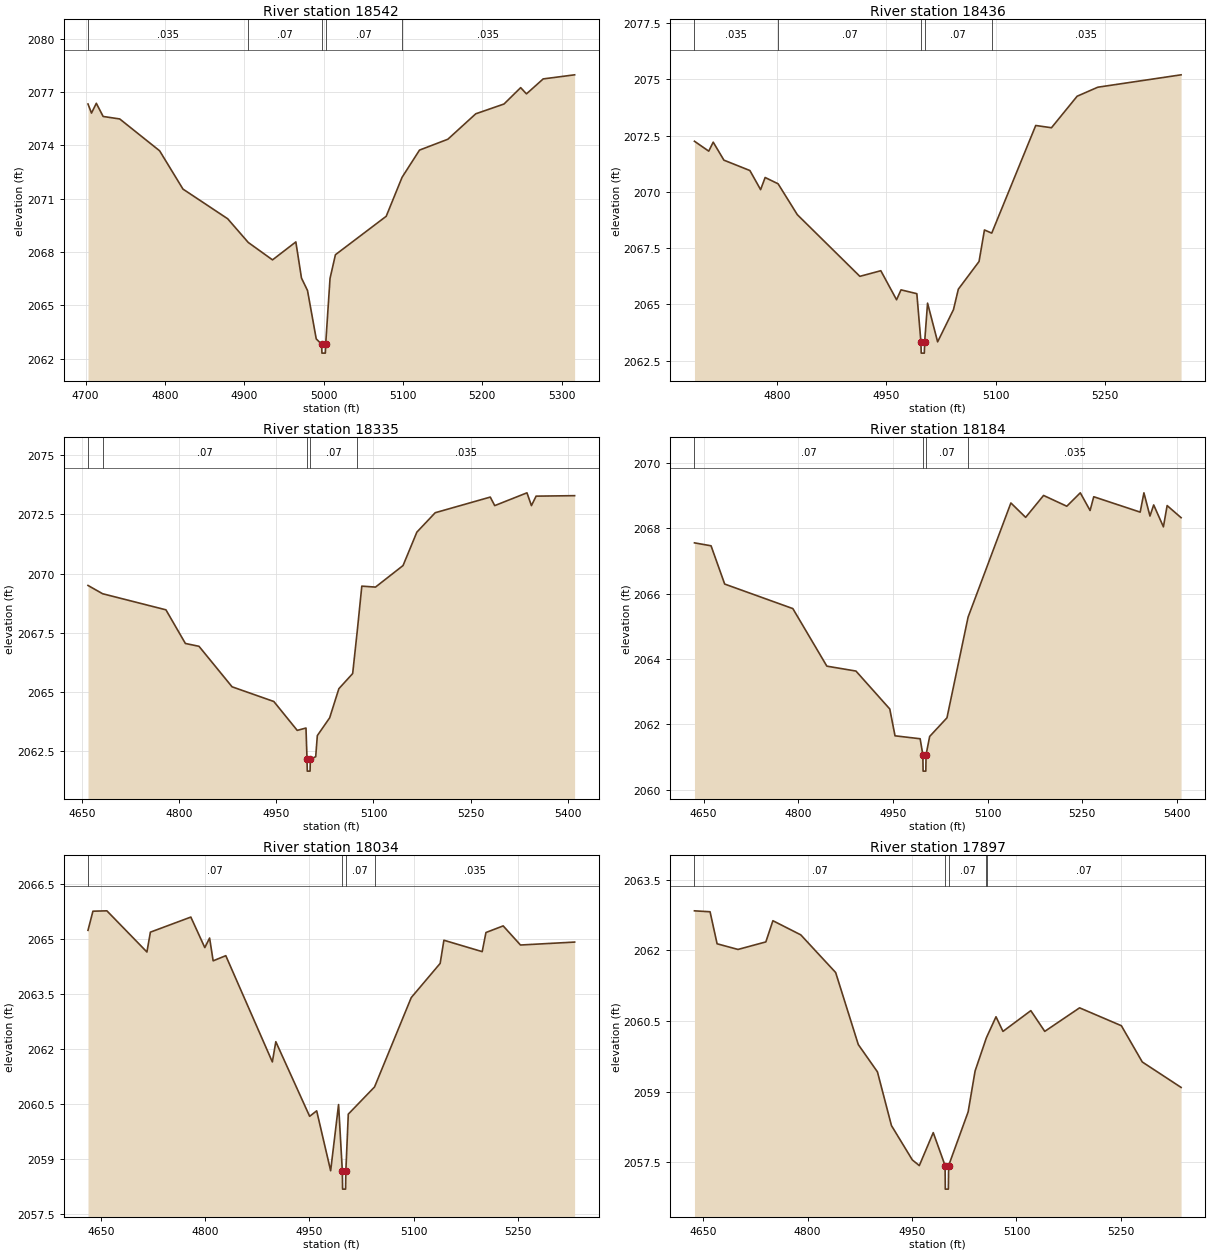
Type RM Length L Ch R = 1,18542,106,106,106
BEGIN DESCRIPTION:
Little Elm Creek A 18542.22
END DESCRIPTION:
XS GIS Cut Line= 3
      1517246.81      6805295.82      1517481.22      6805126.52
      1517718.17      6804905.20
#Sta/Elev= 30
  4703.0 2076.32  4707.4 2075.81  4713.5 2076.36  4722.1 2075.62  4743.0 2075.48
  4793.3 2073.69  4822.7 2071.54  4879.1 2069.87  4905.0 2068.54  4935.6 2067.56
  4965.0 2068.57  4972.1 2066.54  4979.7 2065.84  4990.7 2063.12  4997.5 2062.82
  4997.9 2062.32  5002.2 2062.32  5002.6 2062.82  5008.1 2066.52  5014.9 2067.85
  5078.9 2070.01  5098.9 2072.20  5120.9 2073.73  5156.6 2074.34  5191.8 2075.77
  5227.4 2076.32  5248.4 2077.24  5255.7 2076.89  5276.8 2077.73  5316.4 2077.96
#Mann=5,-1,0
  4703.0   0.035       0  4905.0    0.07       0  4997.5    0.07       0
  5002.6    0.07       0  5098.9   0.035       0
Bank Sta=4997.5,5002.6
Exp/Cntr=0.3,0.1

Type RM Length L Ch R = 1,18436,101,101,101
BEGIN DESCRIPTION:
Little Elm Creek A 18436.11
END DESCRIPTION:
XS GIS Cut Line= 3
      1517278.12      6805397.34      1517533.31      6805212.46
      1517793.71      6804975.50
#Sta/Elev= 30
  4687.0 2072.25  4706.6 2071.81  4712.7 2072.21  4727.4 2071.41  4763.0 2070.95
  4777.7 2070.10  4783.9 2070.64  4801.7 2070.36  4828.0 2068.99  4913.8 2066.25
  4942.5 2066.50  4964.1 2065.21  4970.2 2065.65  4991.9 2065.48  4997.5 2063.34
  4997.9 2062.84  5002.2 2062.84  5002.6 2063.34  5006.6 2065.06  5020.4 2063.34
  5042.1 2064.77  5048.8 2065.68  5077.2 2066.91  5084.6 2068.31  5094.6 2068.17
  5154.9 2072.95  5176.5 2072.85  5211.7 2074.25  5240.0 2074.65  5354.2 2075.20
#Mann=5,-1,0
  4687.0   0.035       0  4801.7    0.07       0  4997.5    0.07       0
  5002.6    0.07       0  5094.6   0.035       0
Bank Sta=4997.5,5002.6
Exp/Cntr=0.3,0.1

Type RM Length L Ch R = 1,18335,151,151,151
BEGIN DESCRIPTION:
Little Elm Creek A 18334.91
END DESCRIPTION:
XS GIS Cut Line= 3
      1517317.20      6805478.06      1517611.43      6805280.17
      1517887.45      6804996.34
#Sta/Elev= 30
  4659.7 2069.50  4682.2 2069.15  4779.9 2068.47  4809.9 2067.05  4830.9 2066.93
  4881.9 2065.22  4946.3 2064.60  4982.4 2063.38  4995.9 2063.48  4997.5 2062.16
  4997.9 2061.66  5002.2 2061.66  5002.6 2062.16  5010.9 2062.27  5013.4 2063.16
  5032.4 2063.91  5046.6 2065.14  5067.9 2065.78  5075.1 2067.61  5082.0 2069.47
  5103.1 2069.43  5145.6 2070.34  5166.9 2071.75  5195.2 2072.57  5280.1 2073.23
  5287.0 2072.87  5336.7 2073.41  5343.6 2072.87  5350.8 2073.27  5410.2 2073.29
#Mann=5,-1,0
  4659.7   0.035       0  4682.2    0.07       0  4997.5    0.07       0
  5002.6    0.07       0  5075.1   0.035       0
Bank Sta=4997.5,5002.6
Exp/Cntr=0.3,0.1

Type RM Length L Ch R = 1,18184,150,150,150
BEGIN DESCRIPTION:
Little Elm Creek A 18184.23
END DESCRIPTION:
XS GIS Cut Line= 3
      1517340.61      6805548.39      1517673.93      6805412.98
      1518025.48      6805199.45
#Sta/Elev= 30
  4635.6 2067.55  4661.9 2067.46  4683.5 2066.29  4791.5 2065.54  4845.4 2063.78
  4891.5 2063.63  4945.1 2062.47  4953.4 2061.65  4993.2 2061.56  4997.5 2061.07
  4997.9 2060.57  5002.2 2060.57  5002.6 2061.07  5008.3 2061.63  5035.7 2062.20
  5069.2 2065.28  5137.0 2068.77  5160.4 2068.33  5188.8 2069.00  5225.6 2068.67
  5247.0 2069.08  5262.5 2068.54  5268.3 2068.96  5341.9 2068.49  5347.8 2069.08
  5357.4 2068.37  5363.3 2068.71  5378.7 2068.04  5384.6 2068.69  5406.7 2068.32
#Mann=4,-1,0
  4635.6    0.07       0  4997.5    0.07       0  5002.6    0.07       0
  5069.2   0.035       0
Bank Sta=4997.5,5002.6
Exp/Cntr=0.3,0.1

Type RM Length L Ch R = 1,18034,137,137,137
BEGIN DESCRIPTION:
Little Elm Creek A 18034.23
END DESCRIPTION:
XS GIS Cut Line= 3
      1517337.95      6805592.68      1517710.39      6805551.00
      1518015.09      6805436.42
#Sta/Elev= 30
  4631.5 2065.23  4638.6 2065.75  4658.7 2065.76  4716.3 2064.64  4721.3 2065.18
  4779.5 2065.59  4799.6 2064.76  4806.5 2065.02  4811.6 2064.40  4829.8 2064.54
  4896.8 2061.65  4901.8 2062.20  4950.5 2060.17  4960.6 2060.32  4980.7 2058.69
  4992.1 2060.49  4997.5 2058.69  4997.9 2058.19  5002.2 2058.19  5002.6 2058.69
  5006.1 2060.23  5043.9 2060.97  5096.7 2063.40  5138.3 2064.33  5143.7 2064.96
  5198.8 2064.65  5204.2 2065.17  5229.0 2065.35  5253.9 2064.83  5331.8 2064.91
#Mann=4,-1,0
  4631.5    0.07       0  4997.5    0.07       0  5002.6    0.07       0
  5043.9   0.035       0
Bank Sta=4997.5,5002.6
Exp/Cntr=0.3,0.1

Type RM Length L Ch R = 1,17897,232,232,232
BEGIN DESCRIPTION:
Little Elm Creek A 17897.05
END DESCRIPTION:
XS GIS Cut Line= 3
      1517342.57      6805671.66      1517698.45      6805689.02
      1518040.64      6805680.36
#Sta/Elev= 30
  4637.7 2062.84  4660.1 2062.82  4670.2 2062.14  4700.2 2062.02  4740.2 2062.18
  4750.3 2062.63  4790.3 2062.33  4840.4 2061.53  4872.9 2060.00  4900.4 2059.42
  4920.5 2058.28  4950.5 2057.55  4960.5 2057.43  4980.5 2058.13  4997.5 2057.43
  4997.8 2056.93  5002.2 2056.93  5002.6 2057.43  5030.6 2058.57  5040.6 2059.44
  5056.7 2060.14  5057.9 2060.18  5070.6 2060.59  5080.6 2060.28  5120.6 2060.72
  5140.6 2060.28  5190.6 2060.78  5250.6 2060.40  5280.6 2059.63  5336.3 2059.09
#Mann=5,-1,0
  4637.7    0.07       0  4997.5    0.07       0  5002.6    0.07       0
  5056.7   0.035       0  5057.9    0.07       0
Bank Sta=4997.5,5002.6
Exp/Cntr=0.3,0.1

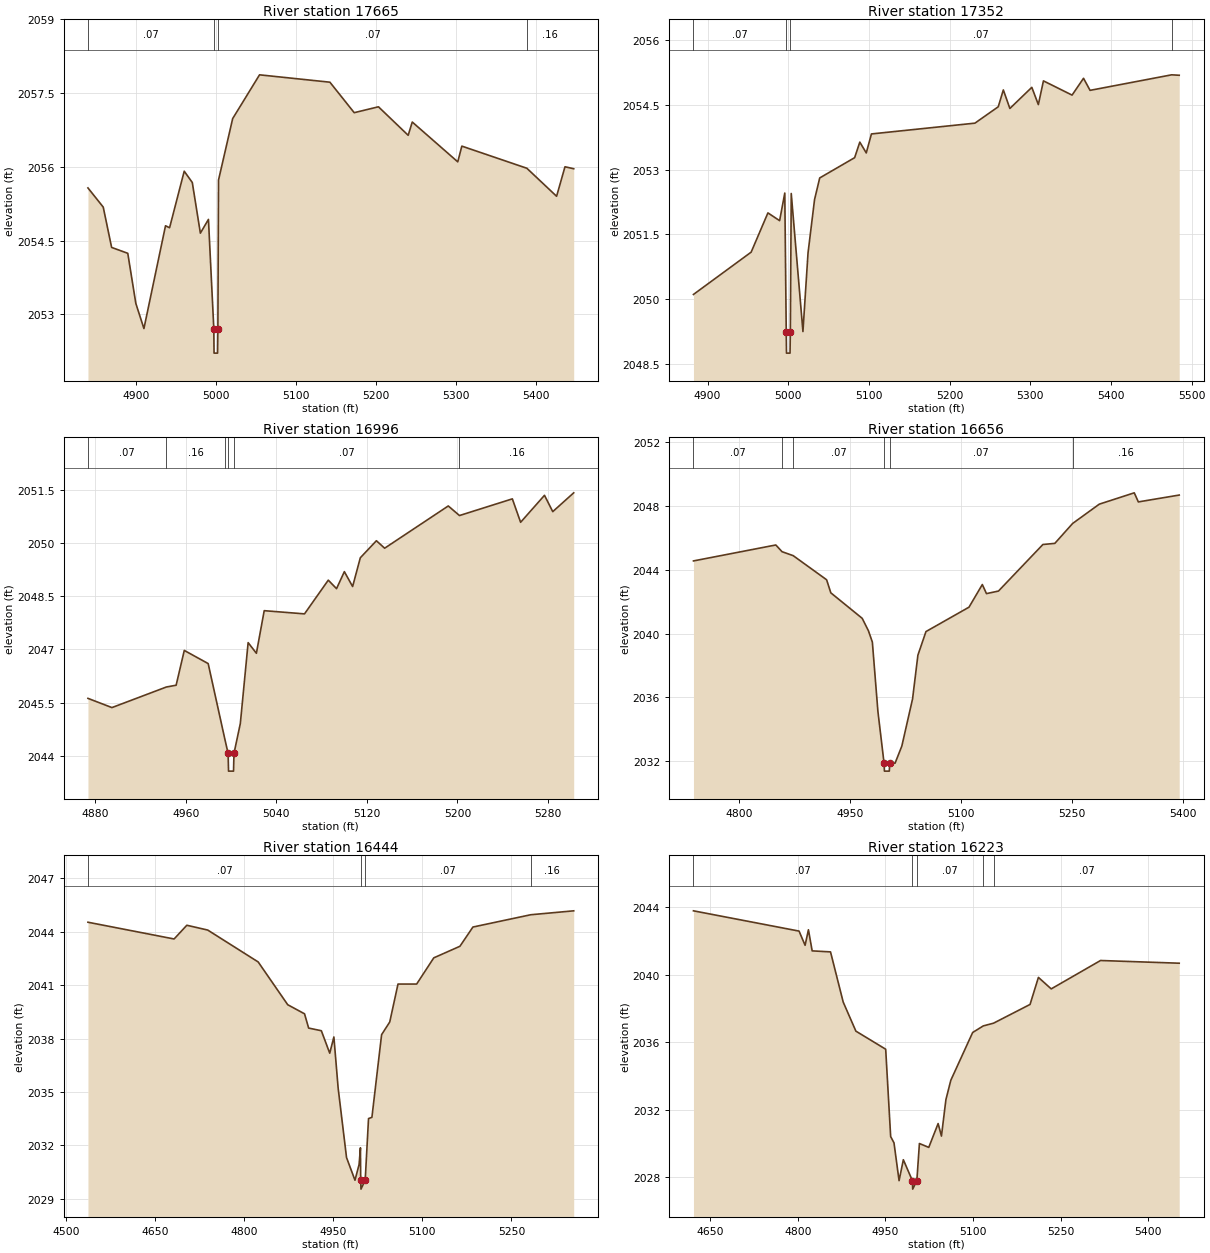
Type RM Length L Ch R = 1,17665,313,313,313
BEGIN DESCRIPTION:
Little Elm Creek A 17665.12
END DESCRIPTION:
XS GIS Cut Line= 3
      1517545.65      6805899.85      1517704.96      6805921.23
      1518146.09      6805850.51
#Sta/Elev= 30
  4840.1 2055.57  4859.2 2055.18  4869.7 2054.36  4889.9 2054.24  4900.0 2053.22
  4910.1 2052.71  4937.1 2054.80  4942.2 2054.76  4960.5 2055.91  4970.6 2055.68
  4980.7 2054.65  4990.8 2054.93  4997.5 2052.71  4997.8 2052.21  5002.2 2052.21
  5002.6 2052.71  5003.4 2055.73  5021.1 2056.98  5054.7 2057.87  5142.7 2057.72
  5173.1 2057.10  5203.4 2057.22  5240.6 2056.64  5245.7 2056.91  5302.6 2056.10
  5307.7 2056.42  5389.0 2055.97  5426.2 2055.40  5436.7 2056.00  5447.6 2055.96
#Mann=4,-1,0
  4840.1    0.07       0  4997.5    0.07       0  5002.6    0.07       0
  5389.0    0.16       0
Bank Sta=4997.5,5002.6
Exp/Cntr=0.3,0.1

Type RM Length L Ch R = 1,17352,356,356,356
BEGIN DESCRIPTION:
Little Elm Creek A 17510.86
END DESCRIPTION:
XS GIS Cut Line= 2
      1517636.50      6806259.41      1518109.24      6805886.52
#Sta/Elev= 30
  4882.5 2050.11  4954.0 2051.09  4974.8 2052.00  4989.3 2051.82  4995.7 2052.46
  4997.5 2049.25  4997.8 2048.75  5002.2 2048.75  5002.6 2049.25  5003.7 2052.45
  5018.2 2049.25  5024.5 2051.07  5032.6 2052.31  5039.0 2052.81  5082.3 2053.28
  5088.7 2053.64  5096.7 2053.39  5103.1 2053.83  5231.4 2054.08  5260.3 2054.46
  5266.6 2054.85  5274.7 2054.42  5301.9 2054.91  5310.0 2054.51  5316.3 2055.06
  5351.8 2054.73  5366.0 2055.12  5374.1 2054.84  5475.2 2055.20  5484.6 2055.19
#Mann=4,-1,0
  4882.5    0.07       0  4997.5    0.07       0  5002.6    0.07       0
  5475.2    0.16       0
Bank Sta=4997.5,5002.6
Exp/Cntr=0.3,0.1

Type RM Length L Ch R = 1,16996,340,340,340
BEGIN DESCRIPTION:
Little Elm Creek A 16995.98
END DESCRIPTION:
XS GIS Cut Line= 3
      1517978.85      6806342.06      1518062.39      6806253.69
      1518286.23      6806042.86
#Sta/Elev= 30
  4873.6 2045.62  4894.8 2045.36  4942.9 2045.94  4951.5 2045.99  4958.7 2046.97
  4979.8 2046.60  4994.4 2044.49  4997.4 2044.07  4997.8 2043.57  5002.2 2043.57
  5002.6 2044.07  5008.2 2044.91  5015.1 2047.19  5022.4 2046.89  5029.3 2048.09
  5064.9 2048.00  5085.9 2048.95  5093.2 2048.71  5100.1 2049.19  5107.4 2048.77
  5114.2 2049.58  5128.4 2050.06  5135.7 2049.85  5191.9 2051.04  5201.8 2050.77
  5248.5 2051.24  5255.8 2050.58  5276.9 2051.34  5284.2 2050.88  5302.7 2051.41
#Mann=6,-1,0
  4873.6    0.07       0  4942.9    0.16       0  4994.4    0.07       0
  4997.4    0.07       0  5002.6    0.07       0  5201.8    0.16       0
Bank Sta=4997.4,5002.6
Exp/Cntr=0.3,0.1

Type RM Length L Ch R = 1,16656,212,212,212
BEGIN DESCRIPTION:
Little Elm Creek A 16656.29
END DESCRIPTION:
XS GIS Cut Line= 3
      1518130.10      6806732.84      1518218.64      6806482.86
      1518372.27      6806123.52
#Sta/Elev= 30
  4738.8 2044.56  4850.0 2045.56  4858.4 2045.14  4873.5 2044.89  4918.6 2043.38
  4924.3 2042.56  4966.7 2040.96  4975.1 2040.18  4980.4 2039.47  4987.9 2035.12
  4996.2 2031.88  4996.7 2031.38  5003.3 2031.38  5003.8 2031.88  5011.1 2031.88
  5020.2 2032.95  5034.7 2035.91  5041.9 2038.65  5052.8 2040.13  5110.9 2041.66
  5128.9 2043.08  5134.5 2042.51  5150.7 2042.67  5210.7 2045.59  5226.8 2045.66
  5250.9 2046.91  5286.9 2048.12  5334.1 2048.83  5339.6 2048.26  5394.8 2048.69
#Mann=6,-1,0
  4738.8    0.07       0  4858.4    0.16       0  4873.5    0.07       0
  4996.2    0.07       0  5003.8    0.07       0  5250.9    0.16       0
Bank Sta=4996.2,5003.8
Exp/Cntr=0.3,0.1

Type RM Length L Ch R = 1,16444,221,221,221
BEGIN DESCRIPTION:
Little Elm Creek A 16443.51
END DESCRIPTION:
XS GIS Cut Line= 3
      1518104.04      6806842.25      1518421.76      6806511.51
      1518590.51      6806194.78
#Sta/Elev= 30
  4537.2 2044.53  4682.2 2043.59  4703.6 2044.36  4738.8 2044.09  4823.7 2042.30
  4873.4 2039.90  4901.7 2039.39  4908.6 2038.59  4930.0 2038.44  4944.1 2037.18
  4951.1 2038.09  4958.3 2035.21  4972.4 2031.32  4986.6 2030.05  4993.5 2030.93
  4995.8 2031.87  4996.2 2030.05  4996.7 2029.55  5003.8 2030.05  5009.4 2033.51
  5015.1 2033.58  5031.4 2038.22  5045.1 2038.93  5059.0 2041.06  5090.4 2041.06
  5119.2 2042.53  5163.2 2043.18  5185.1 2044.26  5282.4 2044.95  5354.7 2045.17
#Mann=4,-1,0
  4537.2    0.07       0  4996.2    0.07       0  5003.8    0.07       0
  5282.4    0.16       0
Bank Sta=4996.2,5003.8
Exp/Cntr=0.3,0.1

Type RM Length L Ch R = 1,16223,116,116,116
BEGIN DESCRIPTION:
Little Elm Creek A 16227.39
END DESCRIPTION:
XS GIS Cut Line= 3
      1518127.49      6806868.27      1518560.92      6806627.33
      1518780.58      6806374.13
#Sta/Elev= 30
  4621.6 2043.77  4802.3 2042.57  4812.6 2041.73  4818.3 2042.65  4824.7 2041.40
  4856.1 2041.34  4877.8 2038.37  4899.5 2036.65  4950.5 2035.58  4959.0 2030.41
  4964.7 2030.04  4973.4 2027.80  4980.7 2029.04  4996.2 2027.80  4996.7 2027.30
  5003.8 2027.80  5008.2 2030.00  5024.2 2029.77  5040.2 2031.18  5045.9 2030.44
  5053.5 2032.59  5061.9 2033.74  5099.3 2036.57  5117.5 2036.96  5135.0 2037.12
  5197.5 2038.23  5211.8 2039.83  5233.7 2039.15  5318.1 2040.83  5452.7 2040.67
#Mann=5,-1,0
  4621.6    0.07       0  4996.2    0.07       0  5003.8    0.07       0
  5117.5    0.16       0  5135.0    0.07       0
Bank Sta=4996.2,5003.8
Exp/Cntr=0.3,0.1

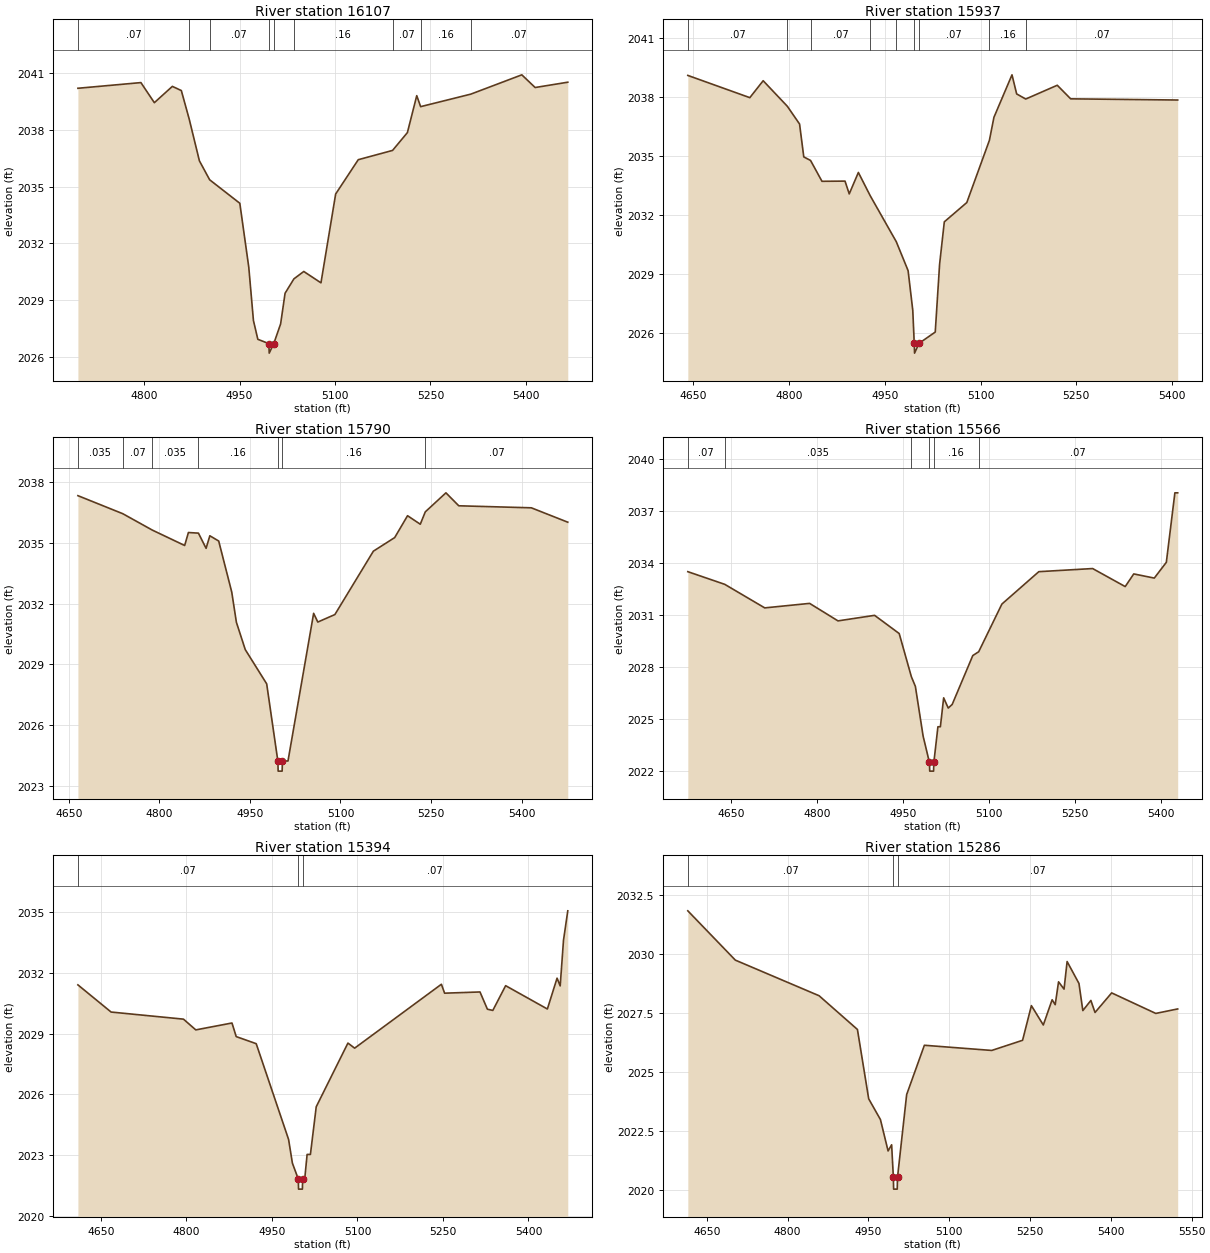
Type RM Length L Ch R = 1,16107,170,170,170
BEGIN DESCRIPTION:
Little Elm Creek A 16106.64
END DESCRIPTION:
XS GIS Cut Line= 3
      1518327.98      6806990.71      1518538.95      6806766.72
      1518812.38      6806394.33
#Sta/Elev= 30
  4696.1 2040.19  4795.1 2040.49  4816.2 2039.43  4844.5 2040.29  4858.6 2040.07
  4871.0 2038.56  4887.0 2036.36  4903.1 2035.36  4950.5 2034.12  4964.6 2030.74
  4971.9 2027.93  4978.8 2026.94  4996.2 2026.71  4996.7 2026.21  5003.8 2026.71
  5014.6 2027.75  5021.6 2029.37  5035.5 2030.13  5051.0 2030.52  5078.0 2029.92
  5101.1 2034.61  5136.6 2036.42  5190.5 2036.91  5213.8 2037.85  5228.5 2039.80
  5234.6 2039.22  5313.4 2039.88  5393.6 2040.90  5414.5 2040.23  5465.8 2040.51
#Mann=9,-1,0
  4696.1    0.07       0  4871.0   0.035       0  4903.1    0.07       0
  4996.2    0.07       0  5003.8    0.07       0  5035.5    0.16       0
  5190.5    0.07       0  5234.6    0.16       0  5313.4    0.07       0
Bank Sta=4996.2,5003.8
Exp/Cntr=0.3,0.1

Type RM Length L Ch R = 1,15937,147,147,147
BEGIN DESCRIPTION:
Little Elm Creek A 15937.25
END DESCRIPTION:
XS GIS Cut Line= 3
      1518408.77      6806998.46      1518682.18      6806761.51
      1518958.24      6806464.61
#Sta/Elev= 30
  4641.6 2039.09  4738.7 2037.96  4759.6 2038.82  4797.5 2037.52  4816.6 2036.62
  4823.2 2034.95  4833.8 2034.77  4851.7 2033.71  4887.8 2033.72  4894.4 2033.07
  4908.7 2034.16  4927.2 2032.98  4968.1 2030.64  4986.6 2029.17  4993.9 2027.16
  4996.2 2025.48  4996.7 2024.98  5003.8 2025.48  5029.1 2026.05  5035.9 2029.49
  5043.3 2031.65  5078.5 2032.63  5113.9 2035.79  5121.0 2036.96  5149.3 2039.12
  5156.6 2038.15  5170.8 2037.89  5220.2 2038.59  5241.2 2037.90  5408.8 2037.84
#Mann=9,-1,0
  4641.6    0.07       0  4797.5   0.035       0  4833.8    0.07       0
  4927.2    0.16       0  4968.1    0.07       0  4996.2    0.07       0
  5003.8    0.07       0  5113.9    0.16       0  5170.8    0.07       0
Bank Sta=4996.2,5003.8
Exp/Cntr=0.3,0.1

Type RM Length L Ch R = 1,15790,224,224,224
BEGIN DESCRIPTION:
Little Elm Creek A 15790.34
END DESCRIPTION:
XS GIS Cut Line= 3
      1518489.49      6807079.20      1518762.91      6806878.69
      1519090.55      6806538.05
#Sta/Elev= 30
  4664.9 2037.33  4739.2 2036.44  4788.2 2035.63  4841.8 2034.87  4848.0 2035.51
  4864.6 2035.48  4877.3 2034.73  4883.5 2035.35  4898.2 2035.09  4919.8 2032.57
  4927.5 2031.08  4942.2 2029.73  4977.7 2028.04  4996.2 2024.23  4996.7 2023.73
  5003.3 2023.73  5003.8 2024.23  5013.0 2024.23  5055.5 2031.52  5062.4 2031.09
  5090.7 2031.46  5154.5 2034.59  5189.8 2035.26  5211.1 2036.34  5232.2 2035.92
  5240.5 2036.53  5274.7 2037.47  5296.0 2036.83  5416.2 2036.73  5476.6 2036.02
#Mann=7,-1,0
  4664.9   0.035       0  4739.2    0.07       0  4788.2   0.035       0
  4864.6    0.16       0  4996.2    0.07       0  5003.8    0.16       0
  5240.5    0.07       0
Bank Sta=4996.2,5003.8
Exp/Cntr=0.3,0.1

Type RM Length L Ch R = 1,15566,172,172,172
BEGIN DESCRIPTION:
Little Elm Creek A 15565.88
END DESCRIPTION:
XS GIS Cut Line= 3
      1518619.70      6807251.07      1518955.61      6806972.44
      1519192.62      6806628.66
#Sta/Elev= 30
  4575.0 2033.51  4639.3 2032.78  4709.1 2031.42  4787.3 2031.68  4836.8 2030.67
  4900.6 2030.99  4943.5 2029.94  4964.7 2027.45  4971.7 2026.89  4985.2 2024.02
  4996.2 2022.50  4996.7 2022.00  5003.4 2022.00  5003.9 2022.50  5011.0 2024.56
  5015.3 2024.56  5021.0 2026.23  5029.0 2025.64  5035.9 2025.85  5071.8 2028.67
  5082.1 2028.89  5122.5 2031.64  5186.9 2033.51  5280.7 2033.69  5337.5 2032.65
  5352.4 2033.38  5388.2 2033.14  5409.2 2034.05  5424.1 2038.06  5429.0 2038.06
#Mann=6,-1,0
  4575.0    0.07       0  4639.3   0.035       0  4964.7    0.16       0
  4996.2    0.07       0  5003.9    0.16       0  5082.1    0.07       0
Bank Sta=4996.2,5003.9
Exp/Cntr=0.3,0.1

Type RM Length L Ch R = 1,15394,108,108,108
BEGIN DESCRIPTION:
Little Elm Creek A 15393.84
END DESCRIPTION:
XS GIS Cut Line= 3
      1518799.35      6807334.44      1519096.24      6807060.99
      1519295.90      6806651.28
#Sta/Elev= 30
  4609.6 2031.40  4667.8 2030.06  4794.8 2029.71  4816.4 2029.18  4879.9 2029.52
  4887.3 2028.85  4922.4 2028.50  4979.2 2023.78  4985.9 2022.61  4996.2 2021.83
  4996.7 2021.33  5003.4 2021.33  5003.9 2021.83  5007.5 2021.83  5011.7 2023.04
  5017.5 2023.04  5027.7 2025.39  5083.3 2028.53  5095.1 2028.28  5247.3 2031.43
  5252.9 2030.99  5315.0 2031.05  5328.0 2030.20  5337.5 2030.14  5360.0 2031.36
  5433.2 2030.21  5450.2 2031.73  5455.7 2031.35  5461.5 2033.60  5469.0 2035.05
#Mann=3,-1,0
  4609.6    0.07       0  4996.2    0.07       0  5003.9    0.07       0
Bank Sta=4996.2,5003.9
Exp/Cntr=0.3,0.1

Type RM Length L Ch R = 1,15286,206,206,206
BEGIN DESCRIPTION:
Little Elm Creek A 15285.68
END DESCRIPTION:
XS GIS Cut Line= 3
      1518874.85      6807402.16      1519161.34      6807149.53
      1519405.54      6806681.92
#Sta/Elev= 30
  4614.6 2031.82  4702.8 2029.73  4858.3 2028.22  4929.5 2026.79  4950.4 2023.85
  4972.2 2022.97  4986.4 2021.64  4993.0 2021.90  4996.2 2020.52  4996.7 2020.02
  5003.4 2020.02  5003.9 2020.52  5020.9 2024.03  5053.8 2026.12  5178.8 2025.90
  5236.1 2026.33  5252.5 2027.80  5274.6 2026.98  5291.0 2028.05  5296.7 2027.84
  5302.9 2028.81  5313.1 2028.50  5318.8 2029.67  5340.8 2028.74  5348.0 2027.59
  5362.9 2028.02  5370.6 2027.51  5401.5 2028.34  5483.4 2027.47  5524.1 2027.66
#Mann=3,-1,0
  4614.6    0.07       0  4996.2    0.07       0  5003.9    0.07       0
Bank Sta=4996.2,5003.9
Exp/Cntr=0.3,0.1