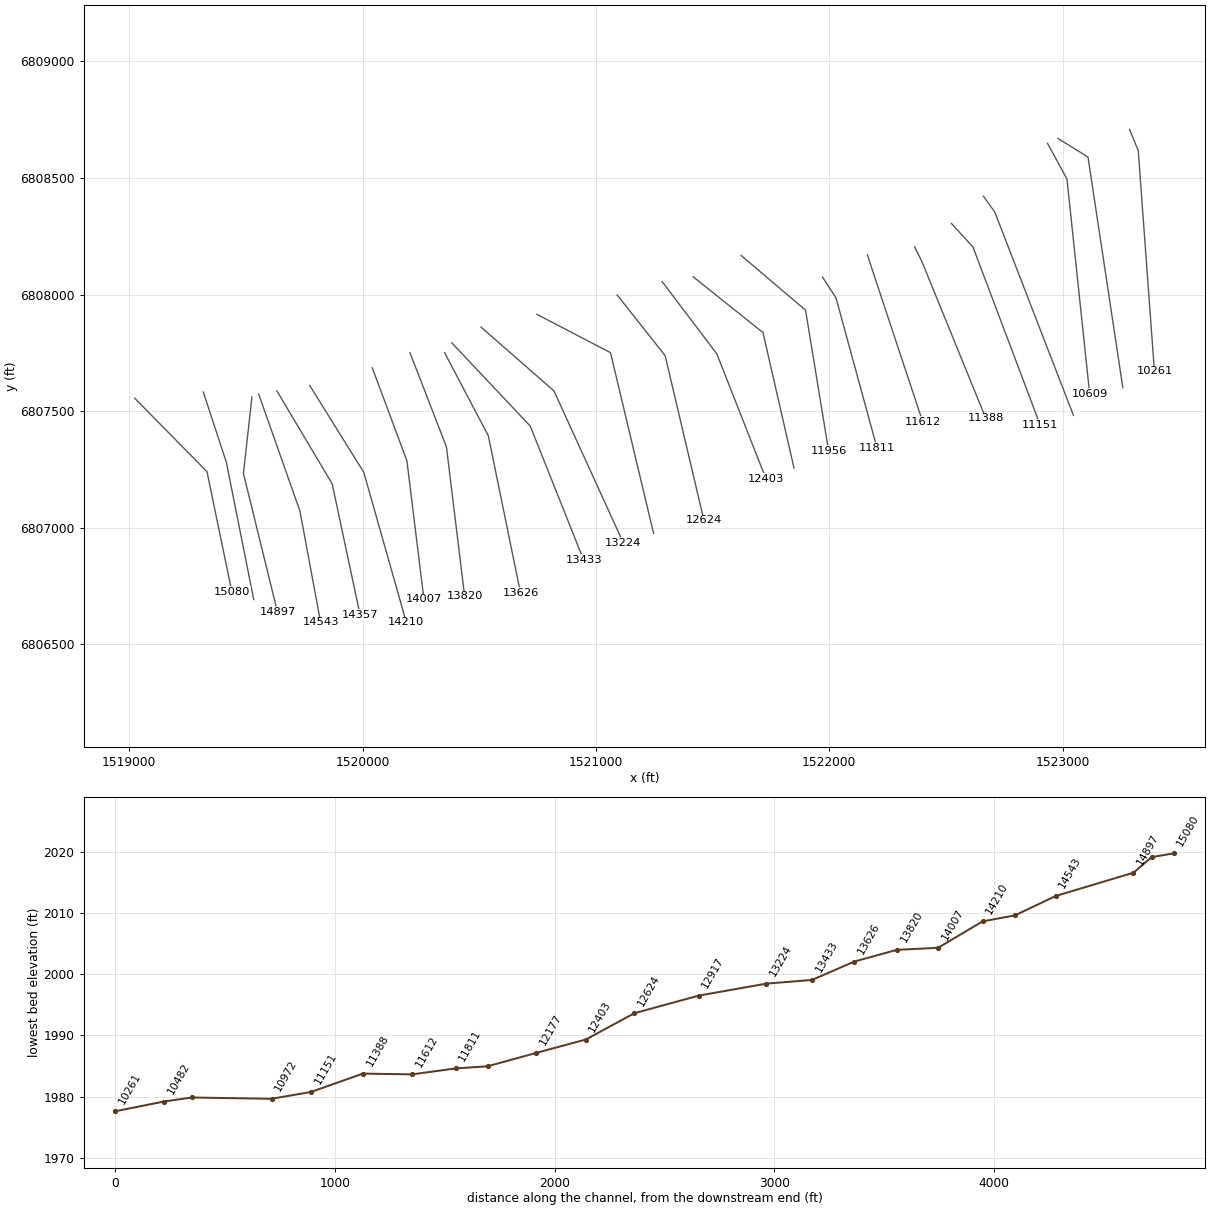
HEC-RAS study Little Elm Creek A.prj: Little Elm Creek A Base Level Engineering

--- Little Elm Creek A.g01 (geometry) --- (continued)

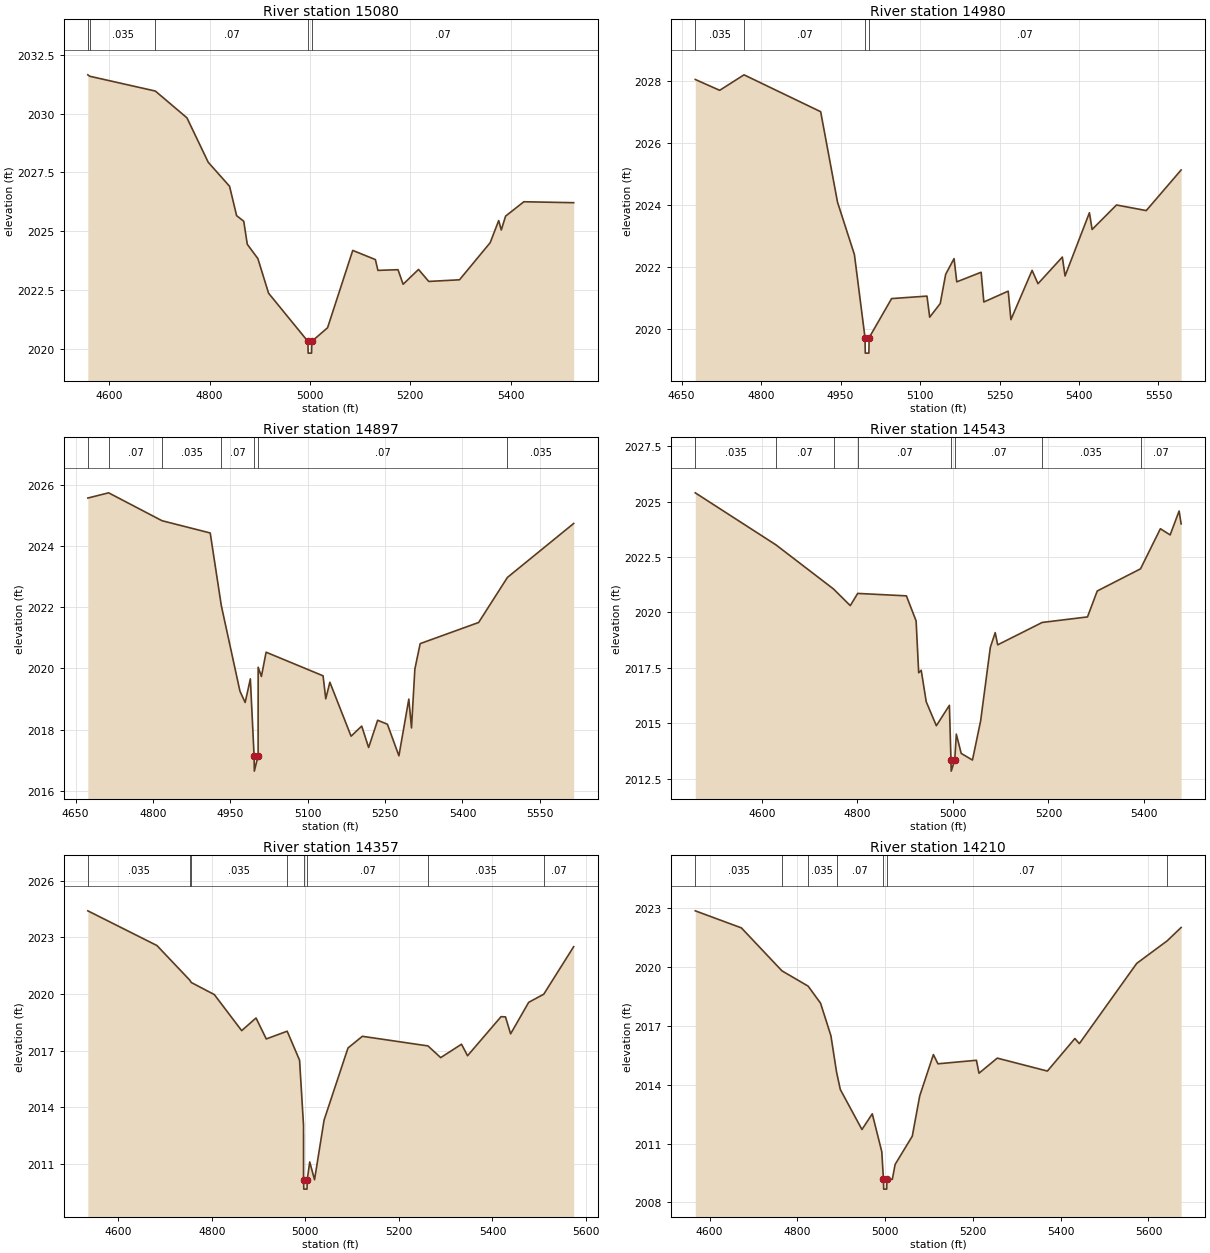
Type RM Length L Ch R = 1,15080,100,100,100
BEGIN DESCRIPTION:
Little Elm Creek A 15079.88
END DESCRIPTION:
XS GIS Cut Line= 3
      1519023.31      6807555.79      1519333.22      6807240.67
      1519439.98      6806725.09
#Sta/Elev= 30
  4557.4 2031.65  4561.1 2031.59  4692.0 2030.96  4755.0 2029.82  4797.4 2027.93
  4839.9 2026.91  4854.0 2025.66  4868.2 2025.42  4875.3 2024.44  4896.4 2023.83
  4917.7 2022.36  4996.1 2020.31  4996.6 2019.81  5003.4 2019.81  5003.9 2020.31
  5035.3 2020.89  5085.5 2024.18  5130.6 2023.79  5135.7 2023.33  5175.7 2023.36
  5185.9 2022.74  5216.6 2023.37  5237.0 2022.86  5298.3 2022.93  5359.5 2024.51
  5376.4 2025.45  5381.6 2025.05  5390.2 2025.64  5426.6 2026.25  5525.9 2026.21
#Mann=5,-1,0
  4557.4    0.07       0  4561.1   0.035       0  4692.0    0.07       0
  4996.1    0.07       0  5003.9    0.07       0
Bank Sta=4996.1,5003.9
Exp/Cntr=0.3,0.1

Type RM Length L Ch R = 1,14980,83,83,83
BEGIN DESCRIPTION:
Little Elm Creek A 14980.33
END DESCRIPTION:
XS GIS Cut Line= 3
      1519317.59      6807581.84      1519416.55      6807279.74
      1519533.57      6806692.07
#Sta/Elev= 30
  4675.7 2028.04  4721.8 2027.69  4767.7 2028.19  4912.4 2027.00  4944.2 2024.08
  4976.1 2022.39  4996.1 2019.71  4996.6 2019.21  5003.4 2019.21  5003.9 2019.71
  5046.3 2020.97  5113.1 2021.05  5118.2 2020.37  5138.1 2020.81  5148.3 2021.75
  5164.2 2022.26  5169.3 2021.51  5215.3 2021.82  5220.4 2020.86  5266.4 2021.21
  5271.5 2020.29  5311.5 2021.88  5322.6 2021.45  5368.6 2022.31  5373.7 2021.70
  5419.7 2023.74  5424.8 2023.20  5470.8 2023.99  5527.0 2023.81  5592.8 2025.12
#Mann=4,-1,0
  4675.7   0.035       0  4767.7    0.07       0  4996.1    0.07       0
  5003.9    0.07       0
Bank Sta=4996.1,5003.9
Exp/Cntr=0.3,0.1

Type RM Length L Ch R = 1,14897,354,354,354
BEGIN DESCRIPTION:
Little Elm Creek A 14896.98
END DESCRIPTION:
XS GIS Cut Line= 3
      1519525.93      6807561.03      1519489.47      6807232.86
      1519635.31      6806639.10
#Sta/Elev= 30
  4673.9 2025.56  4714.2 2025.73  4817.7 2024.82  4911.1 2024.42  4932.6 2022.05
  4968.7 2019.26  4978.8 2018.89  4988.9 2019.66  4996.1 2017.15  4996.6 2016.65
  5003.9 2017.15  5004.0 2020.04  5010.3 2019.74  5019.4 2020.53  5129.8 2019.76
  5135.0 2019.01  5143.0 2019.55  5184.1 2017.79  5204.7 2018.12  5218.1 2017.42
  5235.6 2018.31  5254.5 2018.18  5276.8 2017.15  5296.0 2019.00  5301.2 2018.06
  5307.7 2019.98  5318.0 2020.81  5431.3 2021.50  5487.1 2022.97  5615.5 2024.73
#Mann=7,-1,0
  4673.9   0.035       0  4714.2    0.07       0  4817.7   0.035       0
  4932.6    0.07       0  4996.1    0.07       0  5003.9    0.07       0
  5487.1   0.035       0
Bank Sta=4996.1,5003.9
Exp/Cntr=0.3,0.1

Type RM Length L Ch R = 1,14543,186,186,186
BEGIN DESCRIPTION:
Little Elm Creek A 14542.81
END DESCRIPTION:
XS GIS Cut Line= 3
      1519554.57      6807574.01      1519731.66      6807071.40
      1519820.10      6806595.34
#Sta/Elev= 30
  4460.8 2025.40  4629.8 2023.05  4750.2 2021.06  4785.3 2020.31  4800.8 2020.86
  4902.8 2020.75  4923.1 2019.62  4928.5 2017.28  4933.8 2017.39  4944.3 2015.97
  4965.5 2014.89  4992.8 2015.81  4996.1 2013.34  4996.6 2012.84  5004.0 2013.34
  5007.3 2014.51  5017.5 2013.64  5041.1 2013.34  5058.2 2015.11  5078.5 2018.43
  5088.7 2019.09  5093.9 2018.54  5187.1 2019.55  5281.9 2019.80  5302.3 2020.97
  5392.9 2021.97  5434.5 2023.78  5454.9 2023.50  5473.7 2024.58  5477.9 2024.00
#Mann=8,-1,0
  4460.8   0.035       0  4629.8    0.07       0  4750.2   0.035       0
  4800.8    0.07       0  4996.1    0.07       0  5004.0    0.07       0
  5187.1   0.035       0  5392.9    0.07       0
Bank Sta=4996.1,5004
Exp/Cntr=0.3,0.1

Type RM Length L Ch R = 1,14357,147,147,147
BEGIN DESCRIPTION:
Little Elm Creek A 14357.16
END DESCRIPTION:
XS GIS Cut Line= 3
      1519632.68      6807587.06      1519869.68      6807188.59
      1519989.46      6806626.12
#Sta/Elev= 30
  4534.9 2024.41  4682.7 2022.57  4752.7 2020.74  4756.2 2020.61  4805.4 2019.97
  4863.8 2018.06  4894.5 2018.73  4916.4 2017.62  4961.1 2018.03  4987.6 2016.49
  4996.0 2013.05  4996.1 2010.16  4996.6 2009.66  5003.5 2009.66  5004.0 2010.16
  5009.3 2011.10  5019.6 2010.16  5040.0 2013.32  5091.1 2017.14  5121.8 2017.76
  5262.1 2017.25  5289.3 2016.63  5333.8 2017.34  5346.7 2016.73  5418.3 2018.80
  5427.8 2018.79  5438.8 2017.89  5477.4 2019.56  5509.6 2019.99  5573.6 2022.51
#Mann=8,-1,0
  4534.9   0.035       0  4752.7    0.07       0  4756.2   0.035       0
  4961.1    0.07       0  4996.1    0.07       0  5004.0    0.07       0
  5262.1   0.035       0  5509.6    0.07       0
Bank Sta=4996.1,5004
Exp/Cntr=0.3,0.1

Type RM Length L Ch R = 1,14210,203,203,203
BEGIN DESCRIPTION:
Little Elm Creek A 14209.62
END DESCRIPTION:
XS GIS Cut Line= 3
      1519773.35      6807610.42      1520005.09      6807238.07
      1520187.37      6806594.88
#Sta/Elev= 30
  4567.3 2022.87  4672.4 2022.00  4764.8 2019.81  4824.5 2019.03  4852.8 2018.16
  4876.4 2016.50  4889.2 2014.65  4897.8 2013.76  4947.1 2011.72  4970.6 2012.52
  4992.3 2010.59  4996.1 2009.18  4996.6 2008.68  5003.5 2008.68  5004.0 2009.18
  5016.3 2009.18  5022.7 2009.94  5061.8 2011.38  5078.7 2013.43  5109.9 2015.54
  5120.3 2015.07  5207.9 2015.25  5213.8 2014.59  5255.4 2015.36  5369.7 2014.70
  5432.3 2016.36  5442.5 2016.10  5573.2 2020.19  5642.6 2021.34  5674.4 2022.02
#Mann=7,-1,0
  4567.3   0.035       0  4764.8    0.07       0  4824.5   0.035       0
  4889.2    0.07       0  4996.1    0.07       0  5004.0    0.07       0
  5642.6   0.035       0
Bank Sta=4996.1,5004
Exp/Cntr=0.3,0.1

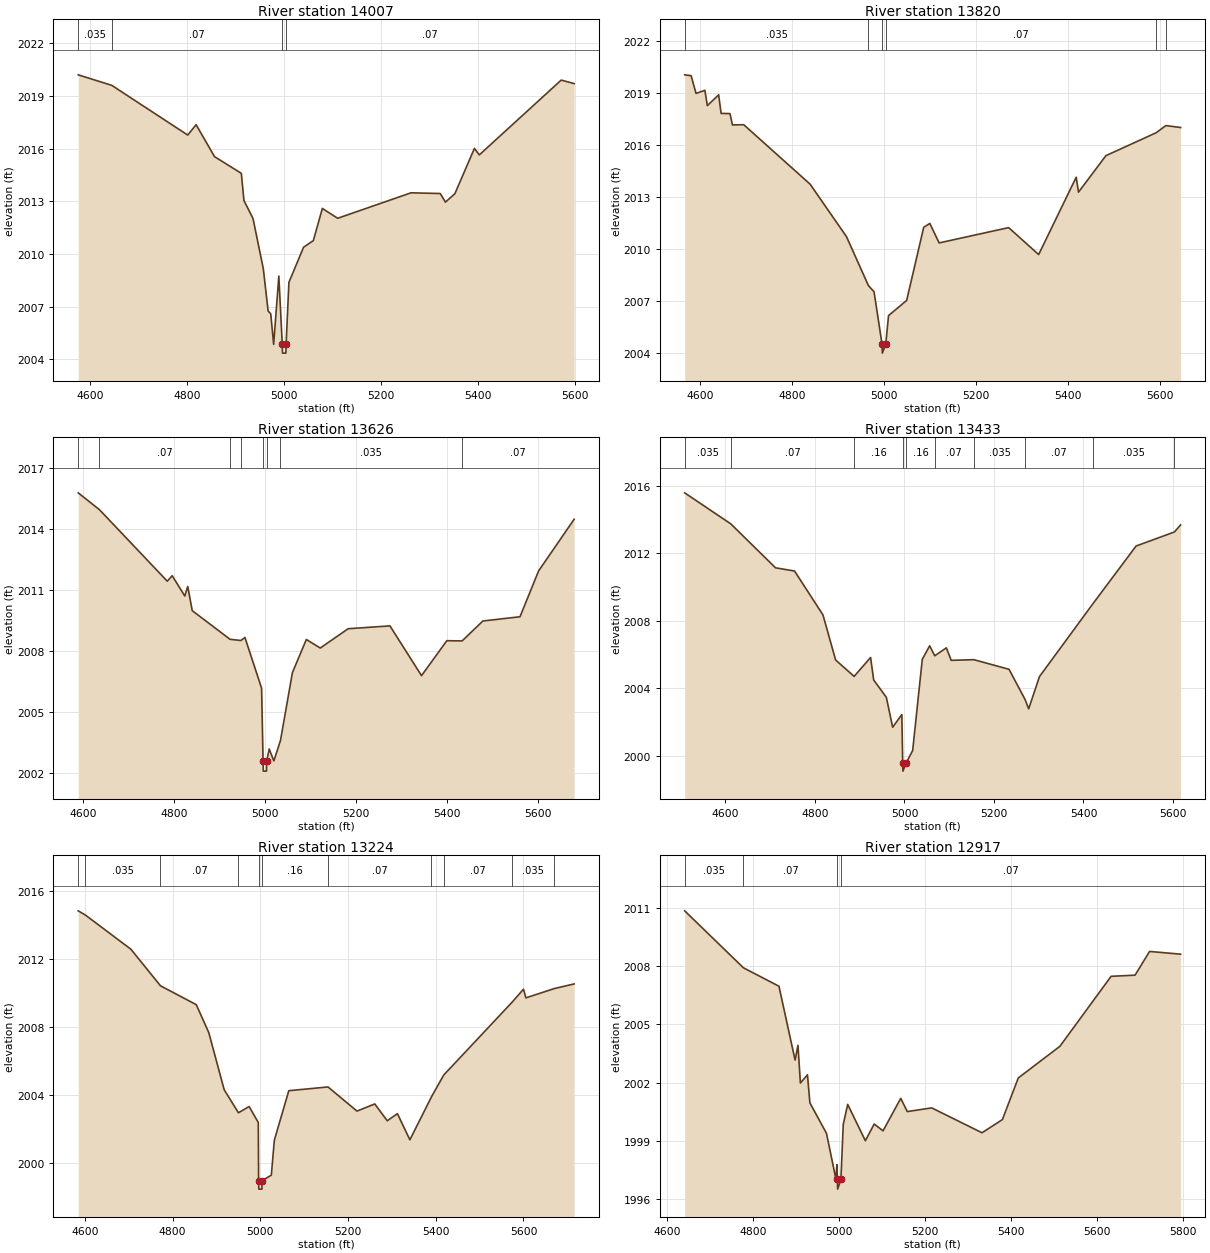
Type RM Length L Ch R = 1,14007,187,187,187
BEGIN DESCRIPTION:
Little Elm Creek A 14006.98
END DESCRIPTION:
XS GIS Cut Line= 3
      1520041.56      6807685.97      1520189.99      6807287.55
      1520262.91      6806693.78
#Sta/Elev= 30
  4575.0 2020.20  4644.3 2019.60  4801.0 2016.77  4818.3 2017.36  4856.3 2015.54
  4911.6 2014.59  4917.0 2013.04  4935.7 2012.02  4957.0 2009.15  4966.9 2006.75
  4972.3 2006.59  4978.3 2004.85  4989.0 2008.74  4996.1 2004.85  4996.6 2004.35
  5003.5 2004.35  5004.0 2004.85  5009.8 2008.38  5040.0 2010.38  5060.2 2010.76
  5078.8 2012.59  5110.5 2012.03  5261.7 2013.48  5322.1 2013.44  5332.8 2012.95
  5352.3 2013.43  5392.6 2016.01  5402.7 2015.64  5571.7 2019.90  5598.4 2019.70
#Mann=4,-1,0
  4575.0   0.035       0  4644.3    0.07       0  4996.1    0.07       0
  5004.0    0.07       0
Bank Sta=4996.1,5004
Exp/Cntr=0.3,0.1

Type RM Length L Ch R = 1,13820,194,194,194
BEGIN DESCRIPTION:
Little Elm Creek A 13820.12
END DESCRIPTION:
XS GIS Cut Line= 3
      1520203.01      6807751.08      1520359.26      6807347.44
      1520437.39      6806706.81
#Sta/Elev= 30
  4566.9 2020.03  4580.9 2019.98  4591.6 2018.96  4610.8 2019.14  4616.2 2018.26
  4640.8 2018.88  4646.1 2017.81  4665.4 2017.80  4670.7 2017.15  4695.3 2017.16
  4839.6 2013.74  4918.7 2010.72  4966.3 2007.91  4978.6 2007.55  4996.1 2004.52
  4996.6 2004.02  5004.0 2004.52  5010.1 2006.18  5049.5 2007.05  5086.6 2011.26
  5099.9 2011.48  5120.1 2010.36  5271.2 2011.24  5336.5 2009.69  5418.1 2014.14
  5423.1 2013.28  5482.7 2015.38  5592.1 2016.70  5613.0 2017.11  5645.1 2017.00
#Mann=6,-1,0
  4566.9   0.035       0  4966.3    0.07       0  4996.1    0.07       0
  5004.0    0.07       0  5592.1   0.035       0  5613.0    0.07       0
Bank Sta=4996.1,5004
Exp/Cntr=0.3,0.1

Type RM Length L Ch R = 1,13626,193,193,193
BEGIN DESCRIPTION:
Little Elm Creek A 13625.86
END DESCRIPTION:
XS GIS Cut Line= 3
      1520351.47      6807751.06      1520538.95      6807394.32
      1520676.64      6806721.46
#Sta/Elev= 30
  4589.8 2015.80  4636.5 2014.97  4785.5 2011.45  4796.3 2011.72  4824.0 2010.72
  4830.5 2011.19  4840.4 2010.00  4923.4 2008.59  4947.3 2008.53  4956.2 2008.68
  4992.8 2006.18  4996.0 2002.60  4996.5 2002.10  5003.5 2002.10  5004.0 2002.60
  5009.5 2003.19  5019.7 2002.60  5034.3 2003.61  5060.5 2006.95  5091.1 2008.58
  5121.7 2008.16  5183.0 2009.11  5274.8 2009.25  5344.2 2006.80  5399.8 2008.52
  5433.4 2008.51  5479.0 2009.49  5560.6 2009.70  5601.6 2011.96  5679.6 2014.50
#Mann=8,-1,0
  4589.8   0.035       0  4636.5    0.07       0  4923.4   0.035       0
  4947.3    0.16       0  4996.0    0.07       0  5004.0    0.16       0
  5034.3   0.035       0  5433.4    0.07       0
Bank Sta=4996,5004
Exp/Cntr=0.3,0.1

Type RM Length L Ch R = 1,13433,209,209,209
BEGIN DESCRIPTION:
Little Elm Creek A 13432.57
END DESCRIPTION:
XS GIS Cut Line= 3
      1520382.71      6807792.75      1520718.64      6807435.99
      1520947.29      6806861.76
#Sta/Elev= 30
  4508.9 2015.57  4612.0 2013.73  4711.9 2011.13  4754.4 2010.94  4817.9 2008.34
  4846.2 2005.67  4887.5 2004.70  4924.3 2005.82  4931.2 2004.49  4959.5 2003.46
  4973.6 2001.69  4994.1 2002.44  4996.0 1999.59  4996.5 1999.09  5004.0 1999.59
  5018.3 2000.31  5039.8 2005.71  5056.3 2006.51  5067.6 2005.92  5093.6 2006.39
  5104.4 2005.65  5155.0 2005.69  5233.6 2005.12  5269.7 2003.32  5277.5 2002.78
  5301.7 2004.69  5420.7 2008.99  5517.5 2012.42  5603.0 2013.25  5617.0 2013.67
#Mann=10,-1,0
  4508.9   0.035       0  4612.0    0.07       0  4887.5    0.16       0
  4996.0    0.07       0  5004.0    0.16       0  5067.6    0.07       0
  5155.0   0.035       0  5269.7    0.07       0  5420.7   0.035       0
  5603.0    0.07       0
Bank Sta=4996,5004
Exp/Cntr=0.3,0.1

Type RM Length L Ch R = 1,13224,307,307,307
BEGIN DESCRIPTION:
Little Elm Creek A 13223.67
END DESCRIPTION:
XS GIS Cut Line= 3
      1520507.67      6807860.49      1520820.20      6807587.03
      1521117.07      6806936.00
#Sta/Elev= 30
  4584.7 2014.85  4601.2 2014.60  4704.9 2012.59  4772.3 2010.44  4853.9 2009.33
  4882.4 2007.69  4917.5 2004.33  4950.0 2002.97  4974.4 2003.34  4995.3 2002.40
  4996.0 1998.98  4996.5 1998.48  5003.5 1998.48  5004.0 1998.98  5025.0 1999.30
  5031.9 2001.36  5064.9 2004.27  5154.3 2004.49  5220.3 2003.07  5260.9 2003.49
  5289.4 2002.50  5312.5 2002.92  5341.0 2001.38  5390.0 2003.90  5418.1 2005.19
  5573.8 2009.47  5600.0 2010.24  5605.5 2009.73  5670.5 2010.28  5715.5 2010.55
#Mann=11,-1,0
  4584.7    0.07       0  4601.2   0.035       0  4772.3    0.07       0
  4950.0    0.16       0  4996.0    0.07       0  5004.0    0.16       0
  5154.3    0.07       0  5390.0   0.035       0  5418.1    0.07       0
  5573.8   0.035       0  5670.5    0.07       0
Bank Sta=4996,5004
Exp/Cntr=0.3,0.1

Type RM Length L Ch R = 1,12917,293,293,293
BEGIN DESCRIPTION:
Little Elm Creek A 12916.82
END DESCRIPTION:
XS GIS Cut Line= 3
      1520747.32      6807915.13      1521062.39      6807751.09
      1521247.29      6806975.03
#Sta/Elev= 30
  4640.9 2010.84  4777.4 2007.91  4860.1 2006.96  4897.6 2003.16  4904.3 2003.92
  4909.9 2001.98  4926.4 2002.40  4932.0 2000.96  4970.6 1999.39  4992.7 1997.02
  4994.8 1997.78  4996.0 1997.02  4996.5 1996.52  5004.1 1997.02  5009.6 1999.85
  5019.9 2000.88  5061.0 1999.01  5081.5 1999.87  5102.1 1999.52  5143.2 2001.19
  5158.5 2000.51  5215.2 2000.70  5332.2 1999.42  5379.6 2000.10  5416.5 2002.24
  5513.3 2003.87  5632.3 2007.47  5688.0 2007.53  5721.7 2008.75  5793.9 2008.61
#Mann=4,-1,0
  4640.9   0.035       0  4777.4    0.07       0  4996.0    0.07       0
  5004.1    0.07       0
Bank Sta=4996,5004.1
Exp/Cntr=0.3,0.1

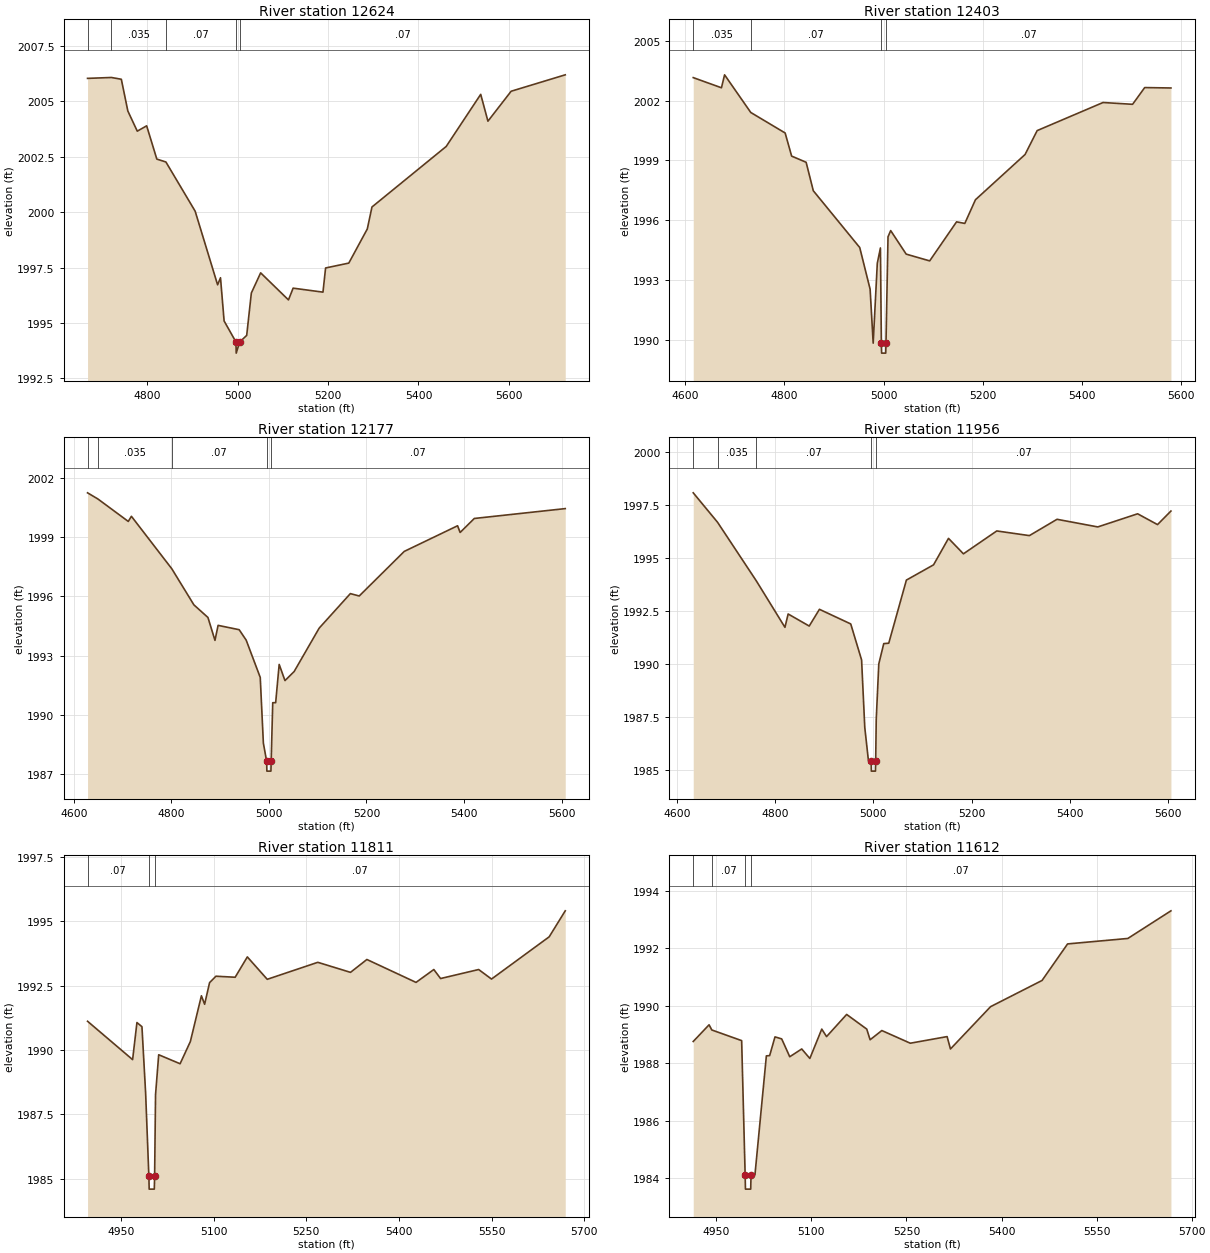
Type RM Length L Ch R = 1,12624,221,221,221
BEGIN DESCRIPTION:
Little Elm Creek A 12624.24
END DESCRIPTION:
XS GIS Cut Line= 3
      1521091.06      6807998.45      1521296.76      6807738.07
      1521463.04      6807031.40
#Sta/Elev= 30
  4667.3 2006.03  4720.1 2006.07  4742.1 2005.99  4756.5 2004.56  4777.4 2003.65
  4798.2 2003.89  4820.7 2002.39  4840.8 2002.26  4905.6 2000.04  4955.3 1996.72
  4961.7 1997.04  4969.7 1995.09  4996.0 1994.14  4996.5 1993.64  5004.1 1994.14
  5019.7 1994.44  5030.0 1996.35  5050.6 1997.26  5112.2 1996.04  5122.5 1996.57
  5188.6 1996.39  5194.4 1997.48  5245.8 1997.70  5286.8 1999.24  5297.1 2000.23
  5461.5 2002.96  5537.9 2005.31  5553.9 2004.10  5605.3 2005.45  5725.1 2006.19
#Mann=5,-1,0
  4667.3    0.07       0  4720.1   0.035       0  4840.8    0.07       0
  4996.0    0.07       0  5004.1    0.07       0
Bank Sta=4996,5004.1
Exp/Cntr=0.3,0.1

Type RM Length L Ch R = 1,12403,226,226,226
BEGIN DESCRIPTION:
Little Elm Creek A 12403.17
END DESCRIPTION:
XS GIS Cut Line= 3
      1521283.72      6808055.81      1521518.11      6807745.88
      1521728.35      6807211.21
#Sta/Elev= 30
  4616.1 2003.16  4673.0 2002.65  4679.3 2003.30  4732.1 2001.41  4801.4 2000.38
  4814.5 1999.22  4843.7 1998.91  4858.2 1997.48  4951.8 1994.63  4972.7 1992.54
  4978.9 1989.83  4987.2 1993.84  4993.5 1994.61  4995.4 1989.83  4995.9 1989.33
  5004.2 1989.33  5004.7 1989.83  5008.8 1995.17  5014.2 1995.48  5045.4 1994.30
  5092.8 1993.96  5147.0 1995.92  5163.6 1995.84  5185.1 1997.03  5285.1 1999.30
  5309.5 2000.50  5442.3 2001.91  5501.9 2001.82  5526.3 2002.66  5579.2 2002.64
#Mann=4,-1,0
  4616.1   0.035       0  4732.1    0.07       0  4995.4    0.07       0
  5004.7    0.07       0
Bank Sta=4995.4,5004.7
Exp/Cntr=0.3,0.1

Type RM Length L Ch R = 1,12177,221,221,221
BEGIN DESCRIPTION:
Little Elm Creek A 12176.67
END DESCRIPTION:
XS GIS Cut Line= 3
      1521416.57      6808076.60      1521716.03      6807837.03
      1521848.84      6807256.32
#Sta/Elev= 30
  4628.3 2001.25  4649.4 2000.94  4711.8 1999.80  4718.2 2000.06  4801.0 1997.40
  4846.3 1995.57  4875.1 1994.93  4889.5 1993.77  4895.9 1994.53  4939.1 1994.31
  4953.5 1993.78  4982.3 1991.89  4988.7 1988.56  4995.4 1987.64  4995.9 1987.14
  5004.2 1987.14  5004.7 1987.64  5007.9 1990.61  5013.9 1990.61  5021.1 1992.55
  5033.0 1991.73  5051.8 1992.19  5103.1 1994.39  5167.0 1996.14  5185.2 1996.02
  5277.5 1998.28  5386.8 1999.58  5392.0 1999.24  5421.1 1999.95  5607.5 2000.45
#Mann=5,-1,0
  4628.3    0.07       0  4649.4   0.035       0  4801.0    0.07       0
  4995.4    0.07       0  5004.7    0.07       0
Bank Sta=4995.4,5004.7
Exp/Cntr=0.3,0.1

Type RM Length L Ch R = 1,11956,145,145,145
BEGIN DESCRIPTION:
Little Elm Creek A 11956.48
END DESCRIPTION:
XS GIS Cut Line= 3
      1521622.30      6808167.74      1521898.32      6807933.38
      1521996.97      6807331.11
#Sta/Elev= 30
  4633.3 1998.09  4682.8 1996.70  4761.8 1993.93  4820.0 1991.74  4826.5 1992.37
  4869.4 1991.80  4890.2 1992.59  4953.9 1991.90  4976.0 1990.20  4982.5 1987.01
  4989.9 1985.45  4995.4 1985.45  4995.9 1984.95  5004.2 1984.95  5004.7 1985.45
  5005.8 1987.38  5011.0 1990.01  5021.1 1990.97  5031.3 1990.99  5067.2 1993.97
  5122.5 1994.69  5152.9 1995.94  5183.3 1995.21  5251.2 1996.29  5317.6 1996.07
  5373.8 1996.84  5456.8 1996.48  5537.9 1997.10  5578.4 1996.59  5605.7 1997.23
#Mann=5,-1,0
  4633.3    0.07       0  4682.8   0.035       0  4761.8    0.07       0
  4995.4    0.07       0  5004.7    0.07       0
Bank Sta=4995.4,5004.7
Exp/Cntr=0.3,0.1

Type RM Length L Ch R = 1,11811,199,199,199
BEGIN DESCRIPTION:
Little Elm Creek A 11811.89
END DESCRIPTION:
XS GIS Cut Line= 3
      1521971.00      6808075.06      1522028.97      6807985.47
      1522204.33      6807342.88
#Sta/Elev= 30
  4896.2 1991.12  4969.1 1989.63  4976.1 1991.07  4984.2 1990.91  4990.2 1988.31
  4995.4 1985.10  4995.9 1984.60  5004.2 1984.60  5004.7 1985.10  5006.2 1988.27
  5011.3 1989.82  5045.9 1989.47  5062.5 1990.33  5080.4 1992.11  5085.6 1991.78
  5093.6 1992.62  5103.9 1992.87  5135.0 1992.83  5154.7 1993.62  5186.9 1992.75
  5268.7 1993.41  5321.6 1993.02  5348.1 1993.52  5427.6 1992.63  5456.4 1993.13
  5467.3 1992.78  5528.9 1993.13  5549.7 1992.76  5643.0 1994.40  5669.0 1995.41
#Mann=3,-1,0
  4896.2    0.07       0  4995.4    0.07       0  5004.7    0.07       0
Bank Sta=4995.4,5004.7
Exp/Cntr=0.3,0.1

Type RM Length L Ch R = 1,11612,224,224,224
BEGIN DESCRIPTION:
Little Elm Creek A 11612.14
END DESCRIPTION:
XS GIS Cut Line= 3
      1522163.58      6808170.66      1522185.22      6808103.52
      1522400.24      6807454.97
#Sta/Elev= 30
  4913.5 1988.76  4938.5 1989.34  4942.8 1989.16  4989.9 1988.79  4995.4 1984.13
  4995.9 1983.63  5004.2 1983.63  5004.7 1984.13  5010.9 1984.13  5028.9 1988.26
  5034.1 1988.27  5042.5 1988.92  5053.1 1988.85  5065.8 1988.23  5084.7 1988.50
  5097.5 1988.17  5116.3 1989.19  5123.9 1988.93  5155.6 1989.70  5187.3 1989.19
  5192.6 1988.82  5211.1 1989.14  5256.0 1988.70  5314.1 1988.93  5319.4 1988.50
  5382.7 1989.97  5463.9 1990.88  5504.2 1992.15  5599.3 1992.34  5667.3 1993.30
#Mann=4,-1,0
  4913.5   0.035       0  4942.8    0.07       0  4995.4    0.07       0
  5004.7    0.07       0
Bank Sta=4995.4,5004.7
Exp/Cntr=0.3,0.1

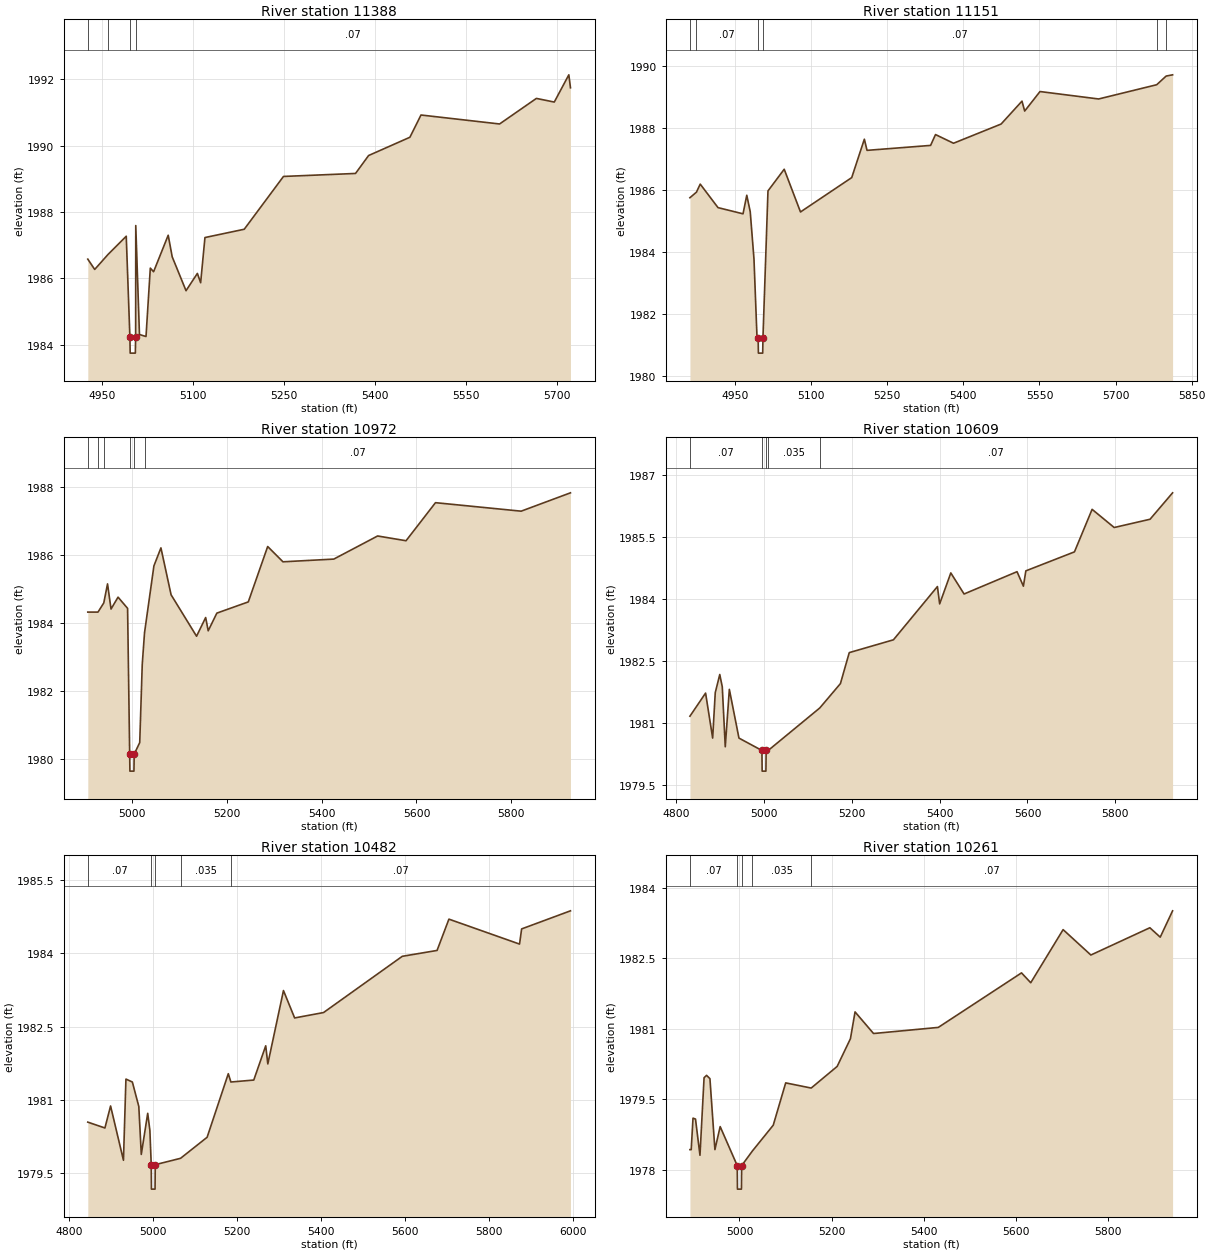
Type RM Length L Ch R = 1,11388,237,237,237
BEGIN DESCRIPTION:
Little Elm Creek A 11388.29
END DESCRIPTION:
XS GIS Cut Line= 3
      1522365.70      6808204.76      1522397.02      6808141.72
      1522670.68      6807469.70
#Sta/Elev= 30
  4925.9 1986.58  4937.3 1986.27  4959.2 1986.72  4989.3 1987.27  4995.3 1984.25
  4995.8 1983.75  5004.3 1983.75  5004.8 1984.25  5005.0 1987.59  5011.1 1984.31
  5021.9 1984.25  5029.0 1986.31  5034.4 1986.20  5058.5 1987.30  5065.1 1986.65
  5087.9 1985.63  5106.6 1986.15  5112.0 1985.87  5119.1 1987.23  5183.9 1987.48
  5248.6 1989.07  5367.4 1989.16  5389.0 1989.70  5457.1 1990.25  5475.4 1990.92
  5605.0 1990.65  5665.7 1991.42  5695.2 1991.31  5719.2 1992.13  5721.9 1991.74
#Mann=4,-1,0
  4925.9   0.035       0  4959.2    0.07       0  4995.3    0.07       0
  5004.8    0.07       0
Bank Sta=4995.3,5004.8
Exp/Cntr=0.3,0.1

Type RM Length L Ch R = 1,11151,179,179,179
BEGIN DESCRIPTION:
Little Elm Creek A 11151.17
END DESCRIPTION:
XS GIS Cut Line= 3
      1522523.57      6808304.93      1522615.77      6808204.22
      1522903.48      6807441.63
#Sta/Elev= 30
  4860.8 1985.76  4873.7 1985.94  4881.1 1986.20  4916.2 1985.44  4965.5 1985.24
  4972.9 1985.84  4979.7 1985.31  4987.1 1983.78  4993.1 1981.24  4995.3 1981.24
  4995.8 1980.74  5004.3 1980.74  5004.8 1981.24  5014.7 1985.98  5046.7 1986.68
  5078.8 1985.30  5179.8 1986.41  5204.7 1987.65  5210.0 1987.29  5335.3 1987.45
  5345.0 1987.80  5380.5 1987.52  5474.3 1988.14  5515.5 1988.88  5520.8 1988.56
  5551.0 1989.19  5666.6 1988.95  5781.1 1989.41  5799.7 1989.69  5812.4 1989.73
#Mann=6,-1,0
  4860.8   0.035       0  4873.7    0.07       0  4995.3    0.07       0
  5004.8    0.07       0  5781.1   0.035       0  5799.7    0.07       0
Bank Sta=4995.3,5004.8
Exp/Cntr=0.3,0.1

Type RM Length L Ch R = 1,10972,363,363,363
BEGIN DESCRIPTION:
Little Elm Creek A 10972.3
END DESCRIPTION:
XS GIS Cut Line= 3
      1522660.76      6808421.83      1522709.52      6808353.52
      1523046.12      6807482.53
#Sta/Elev= 30
  4907.0 1984.31  4928.5 1984.31  4940.7 1984.58  4948.6 1985.14  4956.0 1984.40
  4970.8 1984.75  4990.9 1984.42  4995.3 1980.13  4995.8 1979.63  5004.3 1979.63
  5004.8 1980.13  5016.5 1980.47  5021.8 1982.77  5026.6 1983.70  5046.4 1985.67
  5061.2 1986.20  5082.6 1984.82  5136.3 1983.60  5155.5 1984.15  5160.9 1983.76
  5179.1 1984.28  5245.4 1984.61  5286.3 1986.24  5318.5 1985.79  5425.7 1985.87
  5518.1 1986.55  5578.0 1986.41  5640.1 1987.53  5820.7 1987.28  5924.7 1987.82
#Mann=6,-1,0
  4907.0   0.035       0  4928.5    0.07       0  4940.7   0.035       0
  4995.3   0.035       0  5004.8   0.035       0  5026.6    0.07       0
Bank Sta=4995.3,5004.8
Exp/Cntr=0.3,0.1

Type RM Length L Ch R = 1,10609,127,127,127
BEGIN DESCRIPTION:
Little Elm Creek A 10608.72
END DESCRIPTION:
XS GIS Cut Line= 3
      1522935.23      6808648.63      1523018.55      6808495.88
      1523115.78      6807575.70
#Sta/Elev= 30
  4831.2 1981.17  4866.9 1981.73  4883.0 1980.64  4888.9 1981.74  4899.2 1982.18
  4904.9 1981.88  4911.7 1980.43  4921.0 1981.82  4942.9 1980.64  4995.2 1980.34
  4995.7 1979.84  5004.3 1979.84  5004.8 1980.34  5009.4 1980.34  5127.0 1981.37
  5174.0 1981.96  5194.1 1982.71  5294.7 1983.02  5394.9 1984.31  5400.0 1983.89
  5425.4 1984.64  5455.6 1984.13  5576.2 1984.67  5590.7 1984.32  5596.3 1984.69
  5707.0 1985.15  5747.2 1986.18  5797.5 1985.74  5879.2 1985.94  5930.5 1986.58
#Mann=5,-1,0
  4831.2    0.07       0  4995.2    0.07       0  5004.8    0.07       0
  5009.4   0.035       0  5127.0    0.07       0
Bank Sta=4995.2,5004.8
Exp/Cntr=0.3,0.1

Type RM Length L Ch R = 1,10482,221,221,221
BEGIN DESCRIPTION:
Little Elm Creek A 10481.9
END DESCRIPTION:
XS GIS Cut Line= 3
      1522980.39      6808669.47      1523108.83      6808589.63
      1523257.91      6807601.55
#Sta/Elev= 30
  4844.0 1980.55  4884.8 1980.43  4898.3 1980.88  4929.0 1979.77  4934.9 1981.43
  4950.2 1981.37  4965.6 1980.87  4971.5 1979.89  4986.8 1980.73  4992.0 1980.38
  4995.2 1979.68  4995.7 1979.18  5004.3 1979.18  5004.8 1979.68  5065.1 1979.81
  5128.4 1980.24  5178.9 1981.54  5185.1 1981.37  5239.6 1981.41  5268.1 1982.11
  5273.1 1981.74  5310.4 1983.24  5337.0 1982.68  5405.9 1982.79  5593.6 1983.94
  5676.5 1984.06  5704.8 1984.70  5873.1 1984.19  5878.1 1984.50  5994.5 1984.87
#Mann=5,-1,0
  4844.0    0.07       0  4995.2    0.07       0  5004.8    0.07       0
  5065.1   0.035       0  5185.1    0.07       0
Bank Sta=4995.2,5004.8
Exp/Cntr=0.3,0.1

Type RM Length L Ch R = 1,10261,259,259,259
BEGIN DESCRIPTION:
Little Elm Creek A 10260.55
END DESCRIPTION:
XS GIS Cut Line= 3
      1523287.03      6808708.15      1523324.10      6808617.41
      1523393.42      6807671.27
#Sta/Elev= 30
  4892.6 1978.43  4895.4 1978.43  4899.3 1979.10  4904.7 1979.08  4914.4 1978.31
  4923.3 1979.96  4928.7 1980.01  4936.0 1979.94  4946.8 1978.43  4958.2 1978.92
  4995.2 1978.09  4995.7 1977.59  5004.3 1977.59  5004.8 1978.09  5028.0 1978.40
  5073.3 1978.95  5100.3 1979.85  5155.6 1979.74  5211.9 1980.20  5240.7 1980.79
  5250.7 1981.36  5290.8 1980.90  5431.2 1981.03  5611.7 1982.19  5631.7 1981.98
  5701.9 1983.11  5762.1 1982.57  5890.0 1983.15  5912.5 1982.95  5939.3 1983.51
#Mann=5,-1,0
  4892.6    0.07       0  4995.2    0.07       0  5004.8    0.07       0
  5028.0   0.035       0  5155.6    0.07       0
Bank Sta=4995.2,5004.8
Exp/Cntr=0.3,0.1