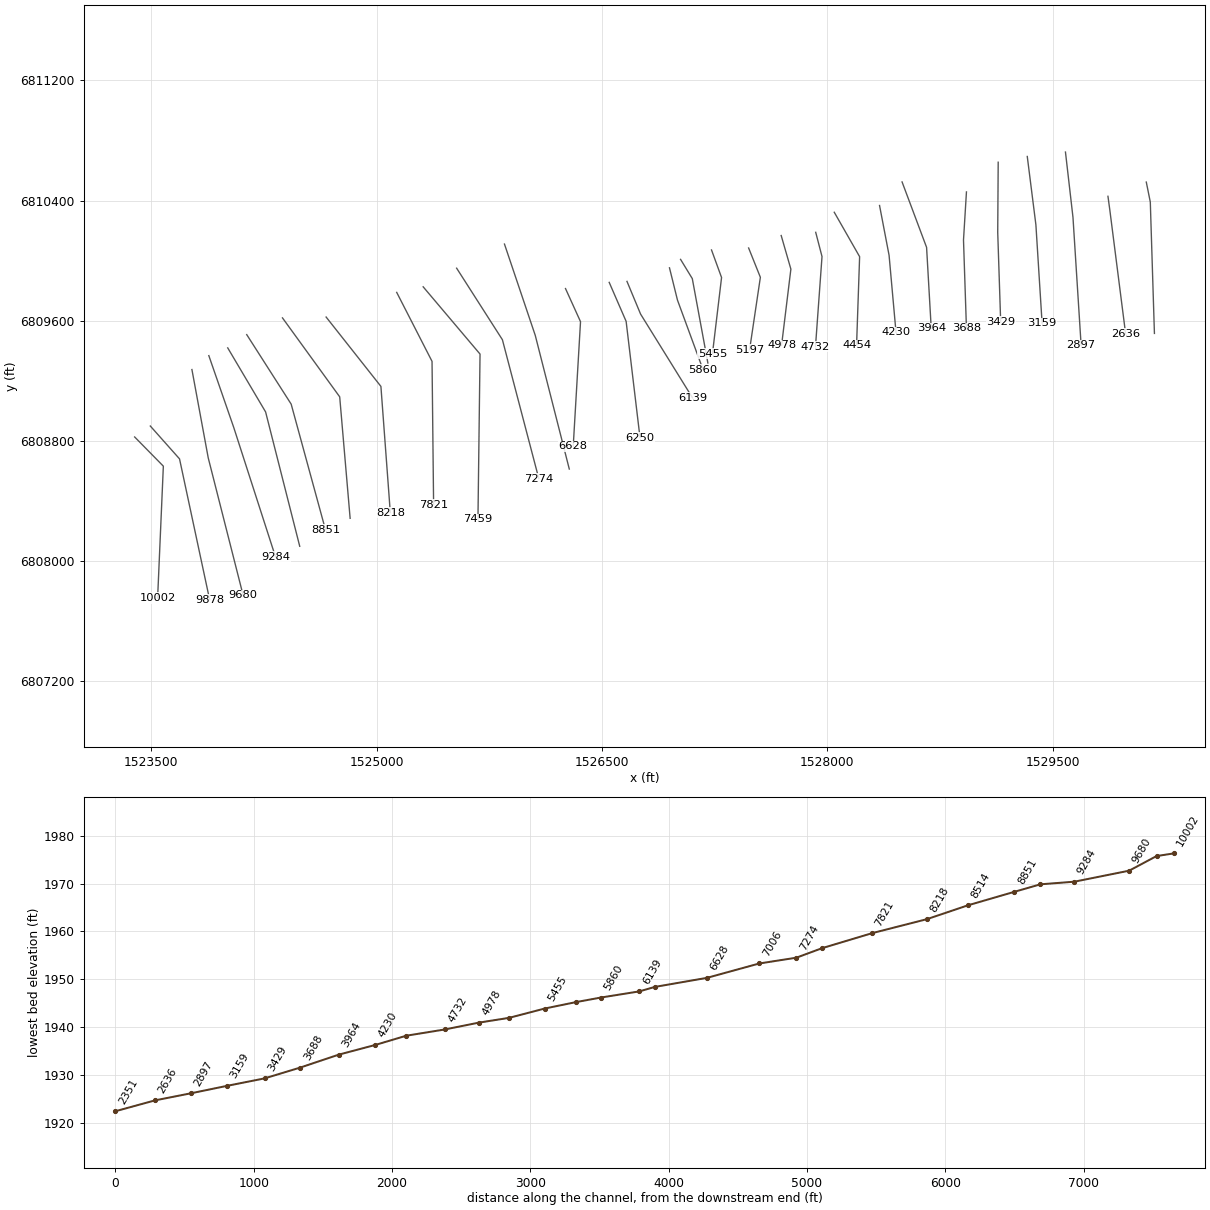
HEC-RAS study Little Elm Creek A.prj: Little Elm Creek A Base Level Engineering

--- Little Elm Creek A.g01 (geometry) --- (continued)

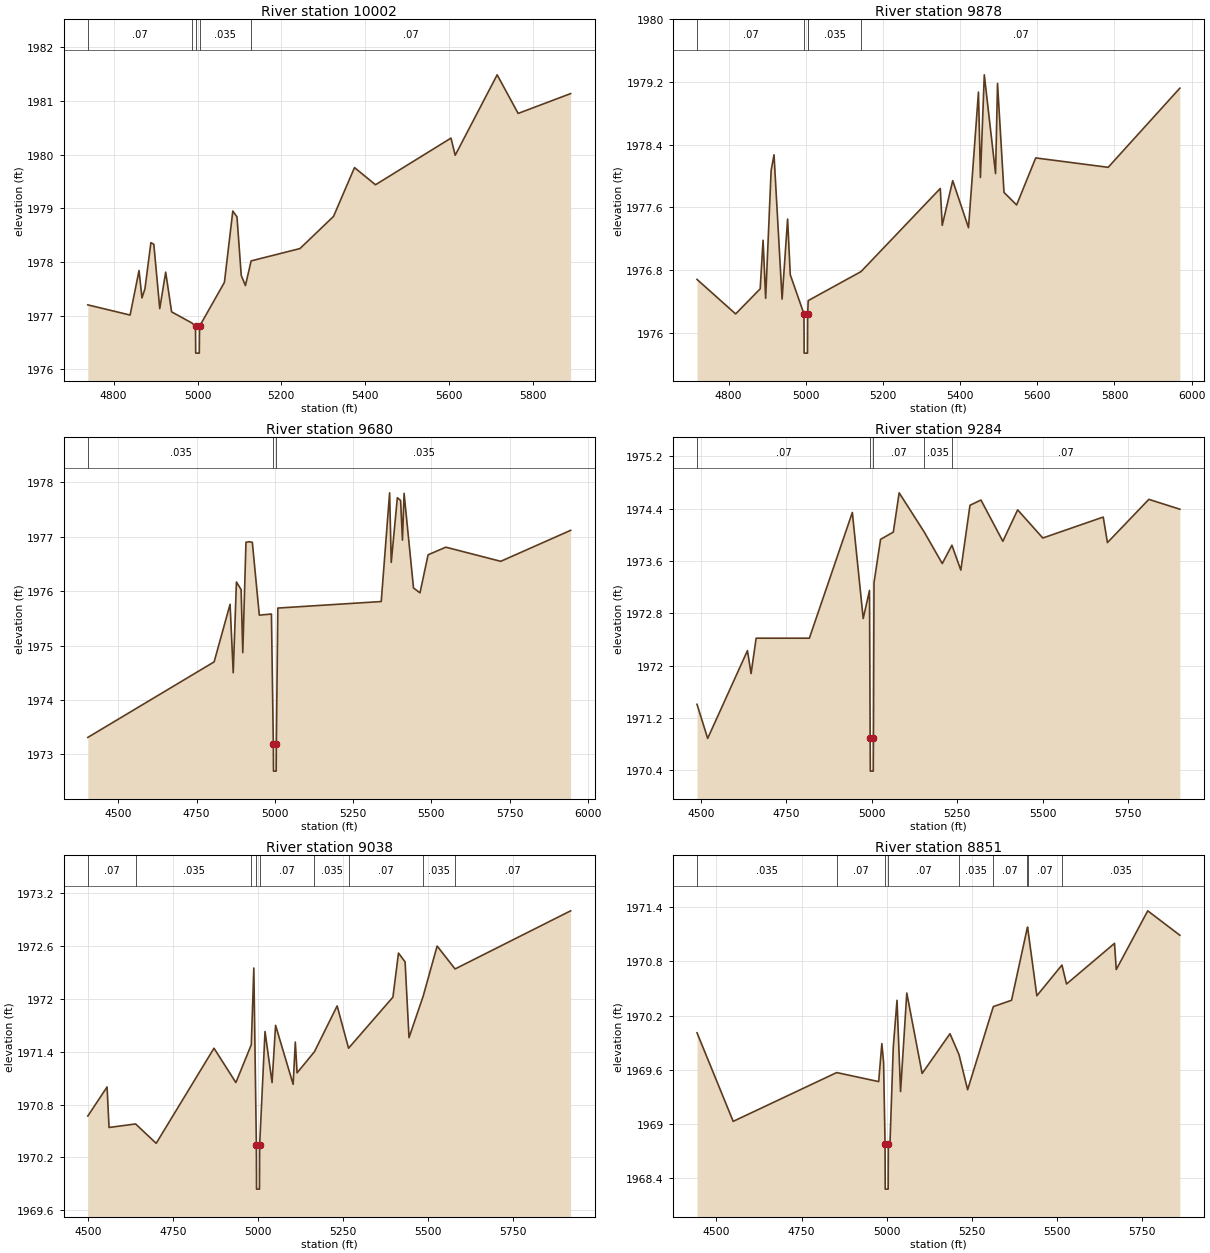
Type RM Length L Ch R = 1,10002,124,124,124
BEGIN DESCRIPTION:
Little Elm Creek A 10002.11
END DESCRIPTION:
XS GIS Cut Line= 3
      1523390.06      6808825.76      1523581.05      6808631.30
      1523542.86      6807752.90
#Sta/Elev= 30
  4738.3 1977.20  4839.2 1977.01  4860.5 1977.84  4867.5 1977.33  4874.6 1977.50
  4888.8 1978.36  4895.8 1978.33  4909.9 1977.13  4924.1 1977.81  4938.2 1977.07
  4987.0 1976.86  4995.2 1976.80  4995.7 1976.30  5004.3 1976.30  5004.8 1976.80
  5064.2 1977.62  5084.2 1978.95  5094.2 1978.84  5104.3 1977.75  5114.3 1977.56
  5127.9 1978.02  5244.4 1978.25  5324.5 1978.85  5374.5 1979.76  5424.6 1979.44
  5604.7 1980.31  5614.7 1979.99  5714.8 1981.49  5764.9 1980.77  5890.1 1981.14
#Mann=5,-1,0
  4738.3    0.07       0  4987.0   0.035       0  4995.2   0.035       0
  5004.8   0.035       0  5127.9    0.07       0
Bank Sta=4995.2,5004.8
Exp/Cntr=0.3,0.1

Type RM Length L Ch R = 1,9878,198,198,198
BEGIN DESCRIPTION:
Little Elm Creek A 9878.38
END DESCRIPTION:
XS GIS Cut Line= 3
      1523494.23      6808898.68      1523688.69      6808679.91
      1523889.05      6807742.28
#Sta/Elev= 30
  4718.0 1976.68  4818.1 1976.24  4881.7 1976.56  4889.2 1977.18  4895.9 1976.44
  4910.1 1978.07  4917.6 1978.27  4938.5 1976.43  4952.8 1977.45  4959.7 1976.74
  4995.2 1976.24  4995.7 1975.74  5004.3 1975.74  5004.8 1976.24  5006.2 1976.41
  5143.1 1976.78  5348.5 1977.84  5353.6 1977.37  5380.8 1977.94  5421.7 1977.34
  5447.5 1979.07  5452.6 1977.98  5462.6 1979.29  5491.8 1978.03  5496.9 1979.18
  5513.7 1977.79  5546.4 1977.63  5595.9 1978.23  5783.7 1978.11  5969.5 1979.12
#Mann=5,-1,0
  4718.0    0.07       0  4995.2    0.07       0  5004.8    0.07       0
  5006.2   0.035       0  5143.1    0.07       0
Bank Sta=4995.2,5004.8
Exp/Cntr=0.3,0.1

Type RM Length L Ch R = 1,9680,396,396,396
BEGIN DESCRIPTION:
Little Elm Creek A 9680.39
END DESCRIPTION:
XS GIS Cut Line= 3
      1523771.15      6809274.80      1523879.66      6808686.85
      1524111.95      6807771.55
#Sta/Elev= 30
  4402.6 1973.31  4806.1 1974.70  4857.0 1975.76  4867.1 1974.50  4877.3 1976.17
  4892.3 1976.03  4897.6 1974.87  4907.8 1976.90  4918.0 1976.91  4928.1 1976.90
  4950.4 1975.56  4989.1 1975.58  4995.2 1973.19  4995.7 1972.69  5004.3 1972.69
  5004.8 1973.19  5009.6 1975.69  5339.8 1975.81  5366.6 1977.81  5371.8 1976.53
  5391.3 1977.72  5401.7 1977.67  5407.6 1976.94  5412.8 1977.80  5442.9 1976.06
  5463.6 1975.97  5489.5 1976.67  5546.1 1976.81  5721.5 1976.55  5944.8 1977.12
#Mann=3,-1,0
  4402.6   0.035       0  4995.2   0.035       0  5004.8   0.035       0
Bank Sta=4995.2,5004.8
Exp/Cntr=0.3,0.1

Type RM Length L Ch R = 1,9284,246,246,246
BEGIN DESCRIPTION:
Little Elm Creek A 9284.29
END DESCRIPTION:
XS GIS Cut Line= 3
      1523883.68      6809367.44      1524049.80      6808888.24
      1524327.72      6808026.32
#Sta/Elev= 30
  4488.6 1971.41  4519.8 1970.89  4636.2 1972.23  4646.8 1971.88  4661.6 1972.42
  4817.3 1972.42  4943.1 1974.34  4974.9 1972.72  4993.3 1973.15  4995.2 1970.89
  4995.7 1970.39  5004.3 1970.39  5004.8 1970.89  5006.5 1973.27  5025.7 1973.93
  5063.0 1974.04  5080.1 1974.64  5153.6 1974.04  5206.2 1973.56  5234.4 1973.84
  5260.5 1973.46  5287.3 1974.45  5319.4 1974.53  5383.5 1973.90  5426.8 1974.38
  5500.4 1973.95  5677.2 1974.27  5689.5 1973.88  5810.7 1974.54  5901.4 1974.39
#Mann=5,-1,0
  4488.6    0.07       0  4995.2    0.07       0  5004.8    0.07       0
  5153.6   0.035       0  5234.4    0.07       0
Bank Sta=4995.2,5004.8
Exp/Cntr=0.3,0.1

Type RM Length L Ch R = 1,9038,187,187,187
BEGIN DESCRIPTION:
Little Elm Creek A 9038.44
END DESCRIPTION:
XS GIS Cut Line= 3
      1524009.55      6809418.97      1524261.60      6808992.41
      1524488.64      6808097.83
#Sta/Elev= 30
  4500.0 1970.67  4556.6 1971.00  4562.4 1970.54  4640.4 1970.58  4700.9 1970.36
  4870.7 1971.44  4935.0 1971.05  4980.3 1971.48  4987.7 1972.35  4995.2 1970.34
  4995.7 1969.84  5004.3 1969.84  5004.8 1970.34  5020.6 1971.63  5041.3 1971.05
  5051.6 1971.70  5103.2 1971.03  5109.6 1971.51  5114.8 1971.16  5165.7 1971.40
  5232.5 1971.92  5266.0 1971.44  5396.3 1972.02  5412.7 1972.52  5432.1 1972.42
  5443.6 1971.56  5485.1 1972.03  5526.2 1972.60  5578.9 1972.34  5918.4 1973.00
#Mann=9,-1,0
  4500.0    0.07       0  4640.4   0.035       0  4980.3    0.07       0
  4995.2    0.07       0  5004.8    0.07       0  5165.7   0.035       0
  5266.0    0.07       0  5485.1   0.035       0  5578.9    0.07       0
Bank Sta=4995.2,5004.8
Exp/Cntr=0.3,0.1

Type RM Length L Ch R = 1,8851,337,337,337
BEGIN DESCRIPTION:
Little Elm Creek A 8853.31
END DESCRIPTION:
XS GIS Cut Line= 3
      1524135.94      6809507.33      1524431.74      6809044.49
      1524660.24      6808206.99
#Sta/Elev= 30
  4443.2 1970.01  4549.4 1969.03  4853.2 1969.57  4976.5 1969.47  4985.8 1969.89
  4990.9 1969.68  4995.2 1968.78  4995.7 1968.28  5004.3 1968.28  5004.8 1968.78
  5009.6 1968.78  5019.3 1969.85  5030.3 1970.37  5040.7 1969.36  5059.0 1970.45
  5104.0 1969.56  5185.8 1970.00  5212.2 1969.77  5237.6 1969.38  5313.0 1970.30
  5366.5 1970.37  5411.5 1971.15  5413.6 1971.18  5440.8 1970.42  5514.5 1970.76
  5527.9 1970.55  5668.8 1971.00  5673.9 1970.71  5766.3 1971.36  5860.6 1971.09
#Mann=9,-1,0
  4443.2   0.035       0  4853.2    0.07       0  4995.2    0.07       0
  5004.8    0.07       0  5212.2   0.035       0  5313.0    0.07       0
  5411.5   0.035       0  5413.6    0.07       0  5514.5   0.035       0
Bank Sta=4995.2,5004.8
Exp/Cntr=0.3,0.1

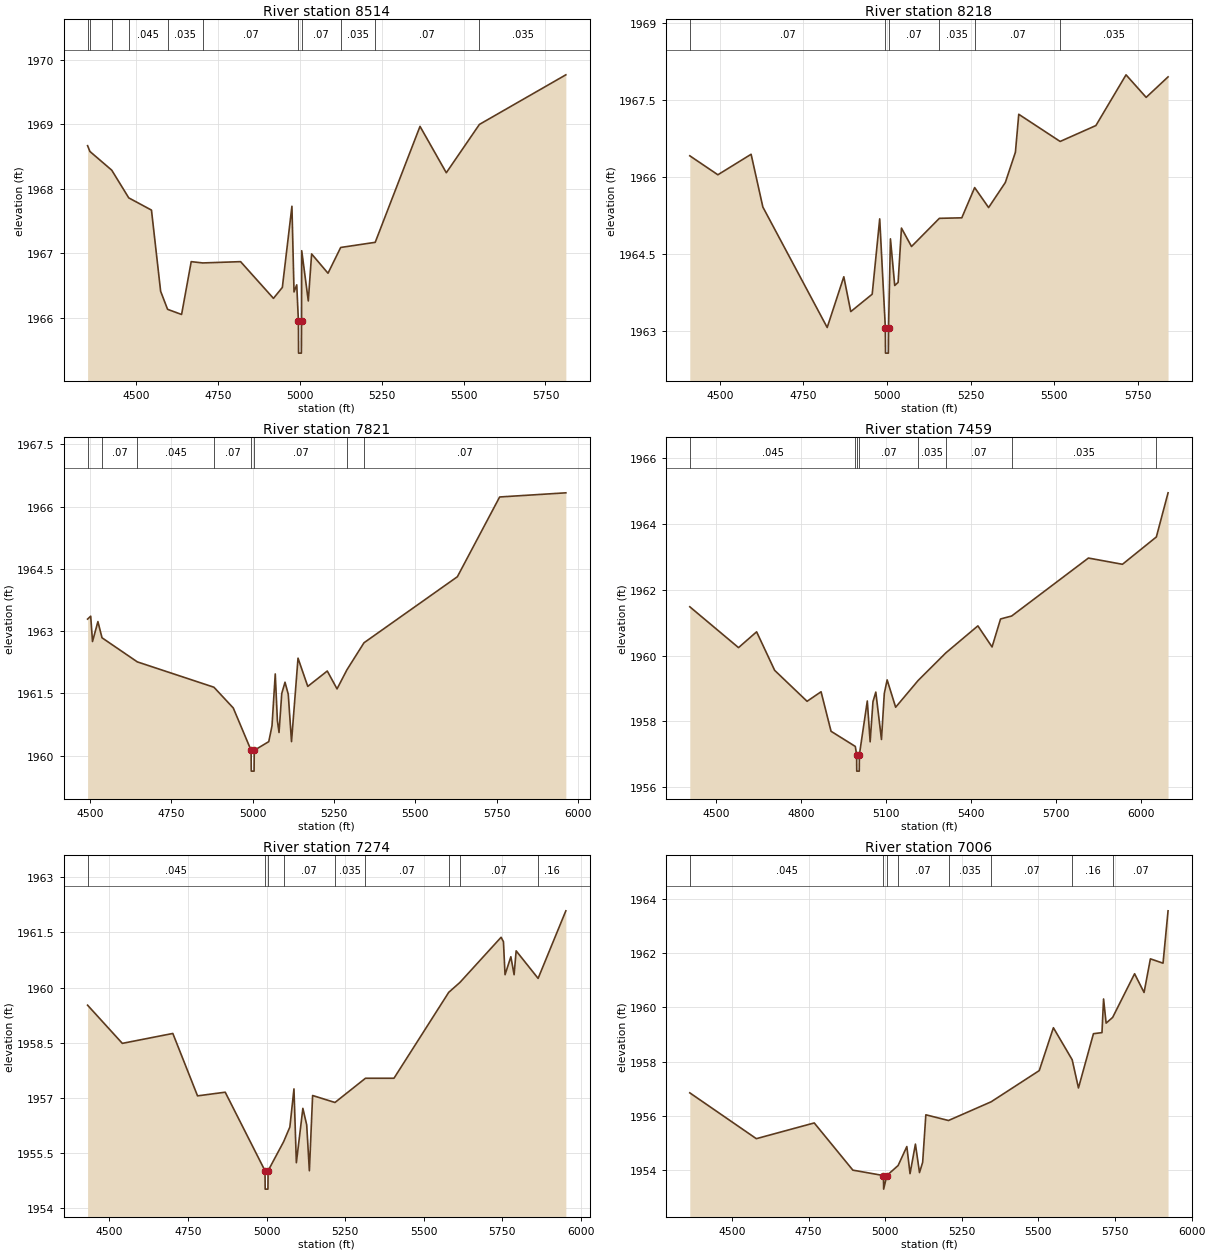
Type RM Length L Ch R = 1,8514,296,296,296
BEGIN DESCRIPTION:
Little Elm Creek A 8513.91
END DESCRIPTION:
XS GIS Cut Line= 3
      1524373.85      6809618.79      1524754.66      6809093.10
      1524824.10      6808284.10
#Sta/Elev= 30
  4351.1 1968.67  4358.3 1968.58  4424.9 1968.29  4476.9 1967.86  4546.3 1967.67
  4574.3 1966.41  4595.5 1966.13  4638.3 1966.05  4667.7 1966.87  4703.0 1966.85
  4818.5 1966.87  4919.0 1966.30  4946.1 1966.47  4975.4 1967.73  4981.8 1966.40
  4990.1 1966.51  4995.2 1965.95  4995.7 1965.45  5004.3 1965.45  5004.8 1965.95
  5005.3 1967.04  5025.4 1966.26  5035.5 1966.99  5085.6 1966.69  5124.3 1967.09
  5229.8 1967.17  5366.7 1968.97  5447.0 1968.25  5548.1 1969.00  5812.2 1969.77
#Mann=11,-1,0
  4351.1    0.07       0  4358.3   0.045       0  4424.9    0.07       0
  4476.9   0.045       0  4595.5   0.035       0  4703.0    0.07       0
  4995.2    0.07       0  5004.8    0.07       0  5124.3   0.035       0
  5229.8    0.07       0  5548.1   0.035       0
Bank Sta=4995.2,5004.8
Exp/Cntr=0.3,0.1

Type RM Length L Ch R = 1,8218,397,397,397
BEGIN DESCRIPTION:
Little Elm Creek A 8217.63
END DESCRIPTION:
XS GIS Cut Line= 3
      1524664.36      6809624.38      1525028.97      6809162.55
      1525091.43      6808322.68
#Sta/Elev= 30
  4410.3 1966.41  4494.3 1966.04  4593.7 1966.44  4628.9 1965.41  4821.3 1963.06
  4871.0 1964.05  4891.8 1963.37  4955.9 1963.71  4978.4 1965.18  4995.2 1963.06
  4995.7 1962.56  5004.3 1962.56  5004.8 1963.06  5010.5 1964.79  5023.3 1963.88
  5033.4 1963.94  5043.4 1965.00  5073.5 1964.64  5156.8 1965.19  5223.9 1965.20
  5262.4 1965.79  5304.1 1965.40  5354.2 1965.89  5384.3 1966.48  5394.3 1967.22
  5518.1 1966.69  5625.0 1967.00  5715.2 1967.99  5775.4 1967.55  5840.9 1967.95
#Mann=6,-1,0
  4410.3    0.07       0  4995.2    0.07       0  5004.8    0.07       0
  5156.8   0.035       0  5262.4    0.07       0  5518.1   0.035       0
Bank Sta=4995.2,5004.8
Exp/Cntr=0.3,0.1

Type RM Length L Ch R = 1,7821,362,362,362
BEGIN DESCRIPTION:
Little Elm Creek A 7823.3
END DESCRIPTION:
XS GIS Cut Line= 3
      1525134.13      6809788.56      1525369.24      6809329.22
      1525379.66      6808374.39
#Sta/Elev= 30
  4492.3 1963.29  4501.9 1963.36  4507.5 1962.75  4524.1 1963.23  4536.7 1962.84
  4645.3 1962.26  4880.9 1961.65  4940.4 1961.15  4995.2 1960.13  4995.7 1959.63
  5004.4 1959.63  5004.9 1960.13  5049.5 1960.34  5059.5 1960.72  5069.5 1961.97
  5076.1 1960.84  5081.1 1960.56  5089.5 1961.50  5099.5 1961.77  5109.5 1961.48
  5119.5 1960.34  5139.5 1962.35  5169.5 1961.67  5229.5 1962.04  5259.5 1961.61
  5290.0 1962.07  5342.4 1962.72  5629.6 1964.31  5759.6 1966.23  5963.2 1966.33
#Mann=8,-1,0
  4492.3   0.045       0  4536.7    0.07       0  4645.3   0.045       0
  4880.9    0.07       0  4995.2    0.07       0  5004.9    0.07       0
  5290.0   0.035       0  5342.4    0.07       0
Bank Sta=4995.2,5004.9
Exp/Cntr=0.3,0.1

Type RM Length L Ch R = 1,7459,185,185,185
BEGIN DESCRIPTION:
Little Elm Creek A 7459.16
END DESCRIPTION:
XS GIS Cut Line= 3
      1525310.22      6809825.74      1525688.69      6809377.83
      1525674.80      6808277.12
#Sta/Elev= 30
  4406.6 1961.48  4578.5 1960.24  4642.3 1960.72  4706.0 1959.55  4820.3 1958.61
  4869.7 1958.90  4904.9 1957.70  4990.5 1957.24  4995.1 1956.99  4995.6 1956.49
  5004.4 1956.49  5004.9 1956.99  5032.8 1958.62  5042.8 1957.38  5052.8 1958.60
  5062.8 1958.89  5082.8 1957.45  5092.8 1958.85  5102.8 1959.26  5132.8 1958.43
  5211.9 1959.24  5309.8 1960.08  5422.9 1960.90  5472.9 1960.26  5502.9 1961.11
  5542.1 1961.20  5812.9 1962.96  5932.9 1962.77  6052.5 1963.60  6093.8 1964.94
#Mann=8,-1,0
  4406.6   0.045       0  4990.5    0.07       0  4995.1    0.07       0
  5004.9    0.07       0  5211.9   0.035       0  5309.8    0.07       0
  5542.1   0.035       0  6052.5    0.07       0
Bank Sta=4995.1,5004.9
Exp/Cntr=0.3,0.1

Type RM Length L Ch R = 1,7274,268,268,268
BEGIN DESCRIPTION:
Little Elm Creek A 7274.09
END DESCRIPTION:
XS GIS Cut Line= 3
      1525532.90      6809949.84      1525837.56      6809473.31
      1526079.75      6808548.80
#Sta/Elev= 30
  4430.7 1959.52  4541.2 1958.48  4701.9 1958.75  4780.5 1957.05  4868.5 1957.15
  4995.1 1955.01  4995.6 1954.51  5004.4 1954.51  5004.9 1955.01  5054.2 1955.80
  5074.1 1956.20  5087.2 1957.24  5094.8 1955.23  5115.5 1956.71  5127.7 1956.26
  5136.2 1955.01  5146.5 1957.06  5217.6 1956.87  5314.7 1957.53  5405.3 1957.53
  5579.5 1959.87  5615.1 1960.14  5746.1 1961.37  5753.5 1961.25  5758.6 1960.35
  5777.1 1960.84  5787.4 1960.35  5793.9 1961.00  5863.8 1960.25  5952.0 1962.09
#Mann=9,-1,0
  4430.7   0.045       0  4995.1   0.045       0  5004.9   0.045       0
  5054.2    0.07       0  5217.6   0.035       0  5314.7    0.07       0
  5579.5   0.035       0  5615.1    0.07       0  5863.8    0.16       0
Bank Sta=4995.1,5004.9
Exp/Cntr=0.3,0.1

Type RM Length L Ch R = 1,7006,378,378,378
BEGIN DESCRIPTION:
Little Elm Creek A 7007.72
END DESCRIPTION:
XS GIS Cut Line= 3
      1525851.25      6810110.48      1526056.31      6809501.96
      1526282.67      6808612.14
#Sta/Elev= 30
  4362.7 1956.85  4579.8 1955.16  4768.7 1955.74  4894.7 1954.00  4994.6 1953.80
  4995.1 1953.30  5005.5 1953.80  5042.3 1954.17  5070.8 1954.87  5081.2 1953.87
  5098.8 1954.96  5112.1 1953.91  5122.4 1954.29  5132.8 1956.04  5206.7 1955.83
  5345.9 1956.52  5502.8 1957.67  5548.9 1959.25  5610.2 1958.07  5630.7 1957.03
  5679.6 1959.03  5707.4 1959.07  5712.6 1960.31  5720.9 1959.42  5742.2 1959.63
  5813.8 1961.24  5844.7 1960.55  5865.4 1961.79  5906.6 1961.63  5923.0 1963.56
#Mann=8,-1,0
  4362.7   0.045       0  4994.6   0.045       0  5005.5   0.045       0
  5042.3    0.07       0  5206.7   0.035       0  5345.9    0.07       0
  5610.2    0.16       0  5742.2    0.07       0
Bank Sta=4994.6,5005.5
Exp/Cntr=0.3,0.1

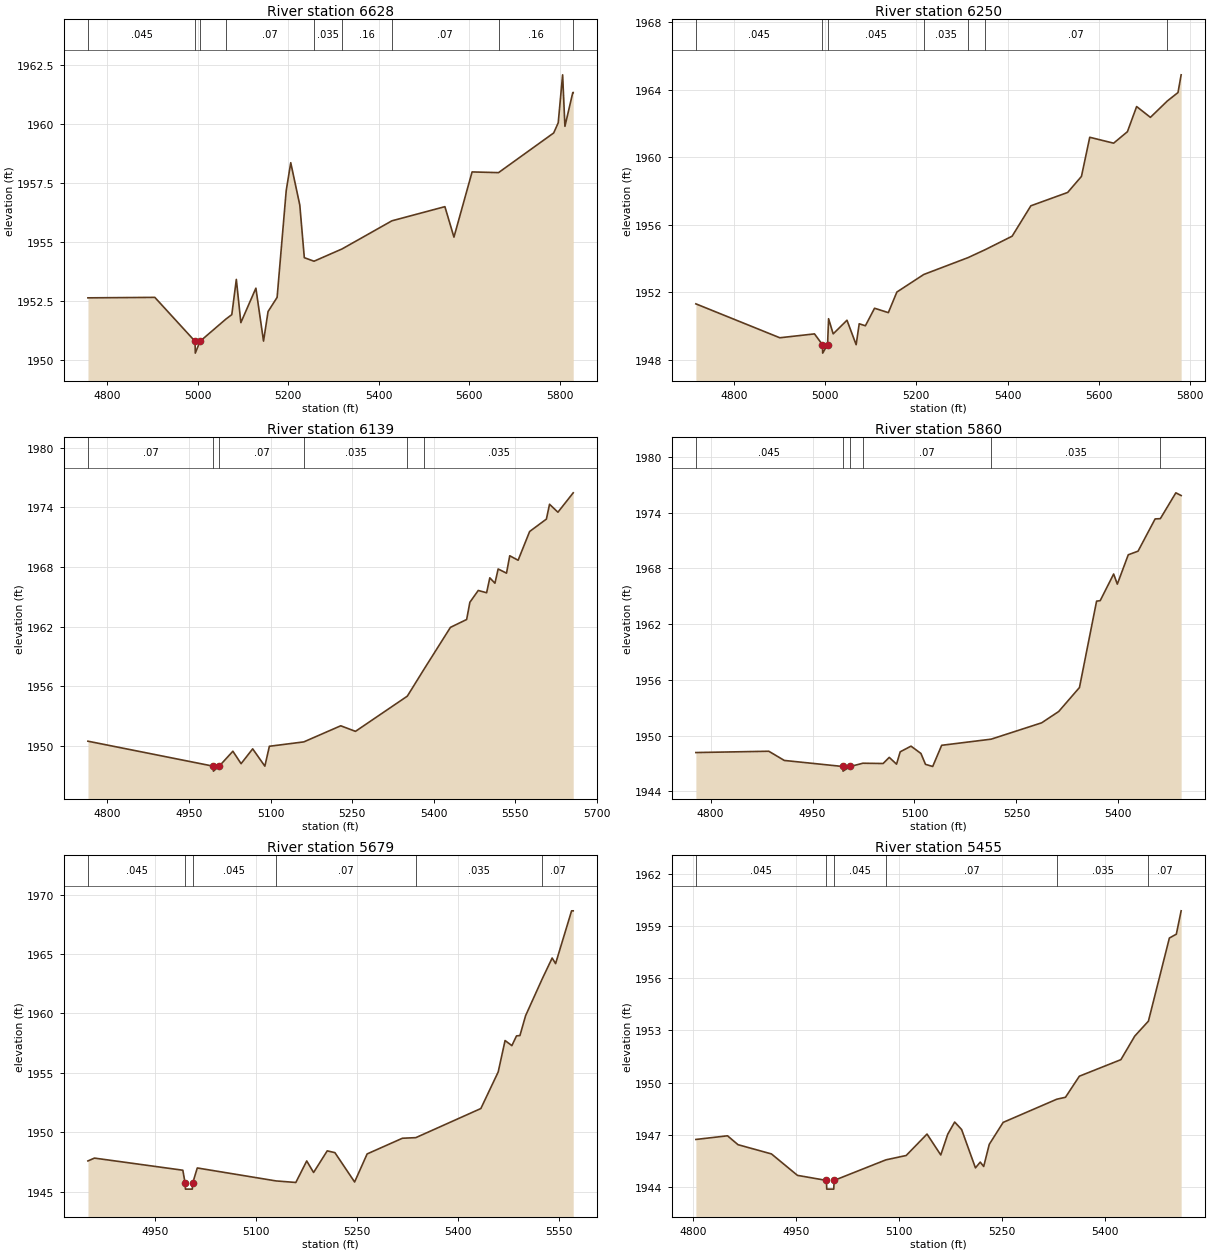
Type RM Length L Ch R = 1,6628,378,378,378
BEGIN DESCRIPTION:
Little Elm Creek A 6628.129
END DESCRIPTION:
XS GIS Cut Line= 3
      1526257.48      6809814.16      1526357.42      6809593.54
      1526308.91      6808764.96
#Sta/Elev= 30
  4757.8 1952.64  4905.6 1952.66  4994.5 1950.80  4995.0 1950.30  5005.5 1950.80
  5062.6 1951.74  5075.7 1951.93  5085.7 1953.42  5095.7 1951.59  5128.9 1953.05
  5145.8 1950.81  5155.8 1952.06  5175.8 1952.66  5195.9 1957.18  5205.9 1958.36
  5225.9 1956.57  5235.9 1954.34  5257.3 1954.19  5319.3 1954.71  5429.4 1955.90
  5546.5 1956.50  5566.5 1955.21  5606.6 1957.97  5665.0 1957.94  5786.9 1959.62
  5796.9 1960.05  5806.6 1962.08  5811.7 1959.90  5829.1 1961.33  5830.0 1961.33
#Mann=9,-1,0
  4757.8   0.045       0  4994.5   0.045       0  5005.5   0.045       0
  5062.6    0.07       0  5257.3   0.035       0  5319.3    0.16       0
  5429.4    0.07       0  5665.0    0.16       0  5829.1    0.07       0
Bank Sta=4994.5,5005.5
Exp/Cntr=0.3,0.1

Type RM Length L Ch R = 1,6250,111,111,111
BEGIN DESCRIPTION:
Little Elm Creek A 6249.664
END DESCRIPTION:
XS GIS Cut Line= 3
      1526548.33      6809855.27      1526660.93      6809595.75
      1526753.35      6808821.14
#Sta/Elev= 30
  4717.1 1951.32  4901.0 1949.31  4976.9 1949.54  4994.4 1948.90  4994.9 1948.40
  5005.6 1948.90  5007.8 1950.44  5017.9 1949.54  5048.1 1950.35  5068.2 1948.90
  5074.9 1950.14  5088.4 1950.02  5108.5 1951.06  5138.7 1950.80  5157.4 1952.02
  5216.3 1953.06  5313.4 1954.06  5350.9 1954.53  5409.9 1955.33  5450.9 1957.13
  5531.5 1957.92  5561.7 1958.87  5579.9 1961.19  5632.2 1960.84  5662.4 1961.52
  5682.6 1963.01  5712.8 1962.37  5749.8 1963.34  5773.2 1963.84  5780.1 1964.89
#Mann=7,-1,0
  4717.1   0.045       0  4994.4    0.07       0  5005.6   0.045       0
  5216.3   0.035       0  5313.4    0.16       0  5350.9    0.07       0
  5749.8    0.16       0
Bank Sta=4994.4,5005.6
Exp/Cntr=0.3,0.1

Type RM Length L Ch R = 1,6139,279,279,279
BEGIN DESCRIPTION:
Little Elm Creek A 6138.633
END DESCRIPTION:
XS GIS Cut Line= 3
      1526666.64      6809861.84      1526757.18      6809644.11
      1527102.96      6809086.17
#Sta/Elev= 30
  4764.2 1950.48  4994.4 1947.97  4994.9 1947.47  5005.6 1947.97  5030.7 1949.47
  5045.8 1948.22  5067.1 1949.71  5089.5 1947.97  5097.8 1949.97  5161.1 1950.41
  5229.0 1952.03  5256.1 1951.47  5351.4 1955.01  5381.9 1957.70  5430.7 1961.93
  5460.5 1962.72  5466.4 1964.45  5481.8 1965.64  5497.2 1965.41  5503.1 1966.91
  5512.5 1966.37  5518.4 1967.80  5533.8 1967.38  5539.7 1969.13  5555.1 1968.68
  5576.3 1971.57  5607.1 1972.82  5612.9 1974.31  5628.3 1973.51  5656.4 1975.46
#Mann=6,-1,0
  4764.2    0.07       0  4994.4    0.07       0  5005.6    0.07       0
  5161.1   0.035       0  5351.4    0.07       0  5381.9   0.035       0
Bank Sta=4994.4,5005.6
Exp/Cntr=0.3,0.1

Type RM Length L Ch R = 1,5860,181,181,181
BEGIN DESCRIPTION:
Little Elm Creek A 5859.947
END DESCRIPTION:
XS GIS Cut Line= 3
      1526949.48      6809952.18      1527002.72      6809737.07
      1527172.42      6809274.94
#Sta/Elev= 30
  4778.4 1948.18  4885.7 1948.32  4908.5 1947.33  4994.4 1946.68  4994.9 1946.18
  5005.6 1946.68  5024.1 1947.03  5053.9 1947.00  5062.9 1947.66  5073.6 1946.93
  5079.0 1948.26  5094.9 1948.87  5109.5 1948.08  5116.2 1946.91  5126.8 1946.68
  5140.0 1948.96  5212.8 1949.62  5287.1 1951.38  5312.2 1952.60  5342.7 1955.18
  5367.9 1964.48  5373.2 1964.53  5393.0 1967.40  5398.4 1966.31  5414.5 1969.47
  5428.9 1969.86  5454.0 1973.33  5461.7 1973.36  5484.5 1976.14  5492.3 1975.85
#Mann=6,-1,0
  4778.4   0.045       0  4994.4   0.045       0  5005.6   0.045       0
  5024.1    0.07       0  5212.8   0.035       0  5461.7    0.07       0
Bank Sta=4994.4,5005.6
Exp/Cntr=0.3,0.1

Type RM Length L Ch R = 1,5679,224,224,224
BEGIN DESCRIPTION:
Little Elm Creek A 5679.151
END DESCRIPTION:
XS GIS Cut Line= 3
      1527023.28      6810008.49      1527101.34      6809880.28
      1527204.96      6809318.36
#Sta/Elev= 30
  4849.9 1947.59  4859.6 1947.83  4991.0 1946.81  4994.4 1945.72  4994.9 1945.22
  5005.1 1945.22  5005.6 1945.72  5012.5 1947.00  5129.6 1945.91  5159.0 1945.78
  5175.2 1947.59  5185.4 1946.62  5205.7 1948.44  5217.1 1948.29  5246.4 1945.82
  5265.0 1948.18  5317.5 1949.50  5337.4 1949.55  5434.1 1952.00  5459.9 1955.08
  5470.1 1957.72  5480.2 1957.29  5487.1 1958.11  5492.2 1958.14  5500.6 1959.81
  5525.7 1962.95  5540.1 1964.66  5545.2 1964.19  5569.0 1968.63  5571.4 1968.63
#Mann=6,-1,0
  4849.9   0.045       0  4994.4   0.045       0  5005.6   0.045       0
  5129.6    0.07       0  5337.4   0.035       0  5525.7    0.07       0
Bank Sta=4994.4,5005.6
Exp/Cntr=0.3,0.1

Type RM Length L Ch R = 1,5455,258,258,258
BEGIN DESCRIPTION:
Little Elm Creek A 5455.363
END DESCRIPTION:
XS GIS Cut Line= 3
      1527229.24      6810071.22      1527296.09      6809887.62
      1527235.57      6809381.02
#Sta/Elev= 30
  4804.6 1946.74  4850.6 1946.95  4865.9 1946.44  4914.5 1945.91  4952.3 1944.68
  4994.4 1944.39  4994.9 1943.89  5005.1 1943.89  5005.6 1944.39  5080.9 1945.57
  5110.4 1945.82  5140.7 1947.05  5160.7 1945.85  5170.8 1947.04  5180.9 1947.74
  5191.0 1947.31  5211.1 1945.11  5218.1 1945.44  5223.1 1945.19  5231.2 1946.46
  5251.4 1947.72  5329.4 1949.05  5342.0 1949.16  5362.2 1950.37  5422.6 1951.32
  5442.7 1952.67  5462.6 1953.53  5493.1 1958.30  5503.2 1958.52  5510.2 1959.86
#Mann=6,-1,0
  4804.6   0.045       0  4994.4   0.045       0  5005.6   0.045       0
  5080.9    0.07       0  5329.4   0.035       0  5462.6    0.07       0
Bank Sta=4994.4,5005.6
Exp/Cntr=0.3,0.1

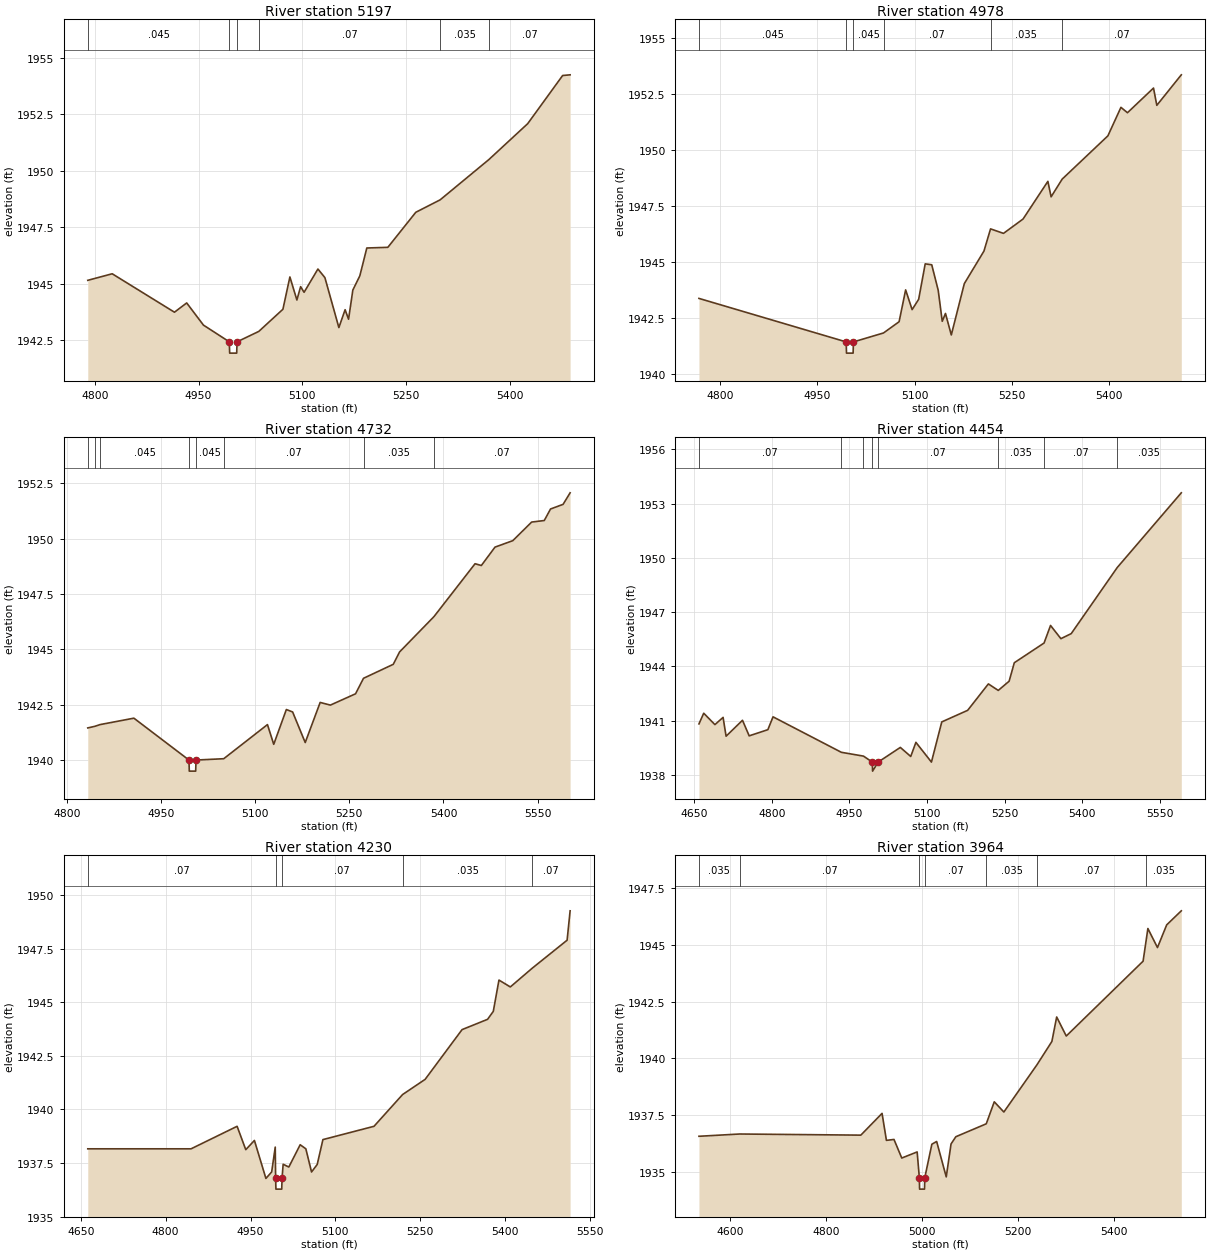
Type RM Length L Ch R = 1,5197,219,219,219
BEGIN DESCRIPTION:
Little Elm Creek A 5197.083
END DESCRIPTION:
XS GIS Cut Line= 3
      1527476.25      6810084.28      1527554.37      6809889.14
      1527482.74      6809407.33
#Sta/Elev= 30
  4789.8 1945.16  4825.1 1945.45  4915.1 1943.75  4932.8 1944.16  4957.0 1943.18
  4994.4 1942.44  4994.9 1941.94  5005.1 1941.94  5005.6 1942.44  5037.0 1942.90
  5071.9 1943.88  5082.0 1945.31  5092.1 1944.29  5097.5 1944.88  5102.5 1944.63
  5122.5 1945.66  5132.6 1945.28  5152.8 1943.07  5161.8 1943.86  5166.8 1943.44
  5173.0 1944.73  5183.1 1945.36  5193.2 1946.59  5223.6 1946.62  5264.0 1948.17
  5299.2 1948.72  5369.6 1950.50  5425.8 1952.09  5476.3 1954.22  5487.1 1954.25
#Mann=6,-1,0
  4789.8   0.045       0  4994.4   0.045       0  5005.6   0.045       0
  5037.0    0.07       0  5299.2   0.035       0  5369.6    0.07       0
Bank Sta=4994.4,5005.6
Exp/Cntr=0.3,0.1

Type RM Length L Ch R = 1,4978,246,246,246
BEGIN DESCRIPTION:
Little Elm Creek A 4977.798
END DESCRIPTION:
XS GIS Cut Line= 3
      1527692.94      6810167.33      1527757.42      6809943.54
      1527695.41      6809435.51
#Sta/Elev= 30
  4767.1 1943.38  4994.4 1941.44  4994.9 1940.94  5005.1 1940.94  5005.6 1941.44
  5052.1 1941.84  5076.1 1942.34  5086.2 1943.76  5096.2 1942.88  5106.3 1943.34
  5116.4 1944.92  5126.5 1944.88  5136.5 1943.74  5142.7 1942.36  5147.7 1942.71
  5156.7 1941.75  5176.8 1944.04  5207.1 1945.49  5217.3 1946.48  5237.3 1946.28
  5267.5 1946.92  5305.8 1948.60  5310.8 1947.91  5327.9 1948.70  5398.5 1950.63
  5418.6 1951.90  5428.7 1951.66  5468.9 1952.76  5474.0 1951.99  5511.8 1953.35
#Mann=6,-1,0
  4767.1   0.045       0  4994.4   0.045       0  5005.6   0.045       0
  5052.1    0.07       0  5217.3   0.035       0  5327.9    0.07       0
Bank Sta=4994.4,5005.6
Exp/Cntr=0.3,0.1

Type RM Length L Ch R = 1,4732,278,278,278
BEGIN DESCRIPTION:
Little Elm Creek A 4732.009
END DESCRIPTION:
XS GIS Cut Line= 3
      1527922.71      6810188.74      1527964.63      6810027.19
      1527921.11      6809426.86
#Sta/Elev= 30
  4833.1 1941.46  4844.1 1941.53  4852.7 1941.61  4906.6 1941.90  4994.4 1940.01
  4994.9 1939.51  5005.1 1939.51  5005.6 1940.01  5049.8 1940.07  5119.5 1941.61
  5129.5 1940.72  5149.6 1942.29  5159.6 1942.18  5179.7 1940.80  5203.5 1942.61
  5219.8 1942.49  5259.9 1943.00  5272.6 1943.70  5320.0 1944.33  5330.1 1944.89
  5384.8 1946.48  5450.4 1948.87  5460.4 1948.79  5482.2 1949.62  5510.5 1949.91
  5540.6 1950.75  5560.7 1950.82  5570.7 1951.34  5590.7 1951.55  5601.9 1952.07
#Mann=8,-1,0
  4833.1   0.045       0  4844.1    0.07       0  4852.7   0.045       0
  4994.4   0.045       0  5005.6   0.045       0  5049.8    0.07       0
  5272.6   0.035       0  5384.8    0.07       0
Bank Sta=4994.4,5005.6
Exp/Cntr=0.3,0.1

Type RM Length L Ch R = 1,4454,224,224,224
BEGIN DESCRIPTION:
Little Elm Creek A 4454.122
END DESCRIPTION:
XS GIS Cut Line= 3
      1528046.18      6810322.27      1528214.91      6810026.52
      1528194.55      6809435.57
#Sta/Elev= 30
  4659.5 1940.82  4668.7 1941.41  4690.3 1940.78  4706.1 1941.18  4711.9 1940.14
  4743.6 1941.02  4756.5 1940.16  4792.6 1940.50  4802.6 1941.21  4934.6 1939.25
  4977.3 1939.04  4994.4 1938.71  4994.9 1938.21  5005.7 1938.71  5048.5 1939.52
  5068.6 1939.02  5078.6 1939.80  5108.6 1938.71  5128.6 1940.93  5178.6 1941.57
  5218.6 1943.03  5237.7 1942.67  5258.7 1943.18  5268.7 1944.20  5326.2 1945.29
  5338.7 1946.26  5358.7 1945.53  5378.7 1945.81  5467.5 1949.46  5591.3 1953.59
#Mann=8,-1,0
  4659.5    0.07       0  4934.6   0.045       0  4977.3    0.07       0
  4994.4    0.07       0  5005.7    0.07       0  5237.7   0.035       0
  5326.2    0.07       0  5467.5   0.035       0
Bank Sta=4994.4,5005.7
Exp/Cntr=0.3,0.1

Type RM Length L Ch R = 1,4230,266,266,266
BEGIN DESCRIPTION:
Little Elm Creek A 4229.516
END DESCRIPTION:
XS GIS Cut Line= 3
      1528347.54      6810367.33      1528410.97      6810035.64
      1528457.10      6809522.71
#Sta/Elev= 30
  4662.3 1938.16  4844.9 1938.16  4926.3 1939.21  4941.6 1938.12  4956.9 1938.55
  4977.2 1936.78  4987.4 1937.08  4993.7 1938.24  4994.4 1936.78  4994.9 1936.28
  5005.2 1936.28  5005.7 1936.78  5007.7 1937.44  5017.7 1937.31  5037.8 1938.35
  5047.8 1938.16  5057.9 1937.08  5067.9 1937.43  5078.0 1938.59  5168.3 1939.21
  5218.8 1940.69  5258.7 1941.40  5324.0 1943.72  5369.1 1944.20  5379.2 1944.57
  5389.2 1946.03  5409.3 1945.71  5448.3 1946.59  5509.7 1947.89  5515.0 1949.26
#Mann=5,-1,0
  4662.3    0.07       0  4994.4    0.07       0  5005.7    0.07       0
  5218.8   0.035       0  5448.3    0.07       0
Bank Sta=4994.4,5005.7
Exp/Cntr=0.3,0.1

Type RM Length L Ch R = 1,3964,276,276,276
BEGIN DESCRIPTION:
Little Elm Creek A 3964.285
END DESCRIPTION:
XS GIS Cut Line= 3
      1528497.44      6810524.30      1528660.59      6810088.43
      1528691.51      6809548.41
#Sta/Elev= 30
  4534.6 1936.57  4619.4 1936.67  4872.3 1936.62  4916.6 1937.58  4925.7 1936.39
  4941.5 1936.43  4957.7 1935.61  4989.8 1935.88  4994.4 1934.74  4994.9 1934.24
  5005.2 1934.24  5005.7 1934.74  5020.5 1936.22  5030.5 1936.34  5050.5 1934.78
  5060.5 1936.23  5070.5 1936.55  5134.0 1937.12  5150.7 1938.09  5170.7 1937.64
  5239.7 1939.72  5270.9 1940.75  5280.9 1941.83  5300.9 1940.99  5461.2 1944.29
  5466.7 1945.08  5471.2 1945.73  5491.2 1944.89  5510.4 1945.89  5540.9 1946.51
#Mann=7,-1,0
  4534.6   0.035       0  4619.4    0.07       0  4994.4    0.07       0
  5005.7    0.07       0  5134.0   0.035       0  5239.7    0.07       0
  5466.7   0.035       0
Bank Sta=4994.4,5005.7
Exp/Cntr=0.3,0.1

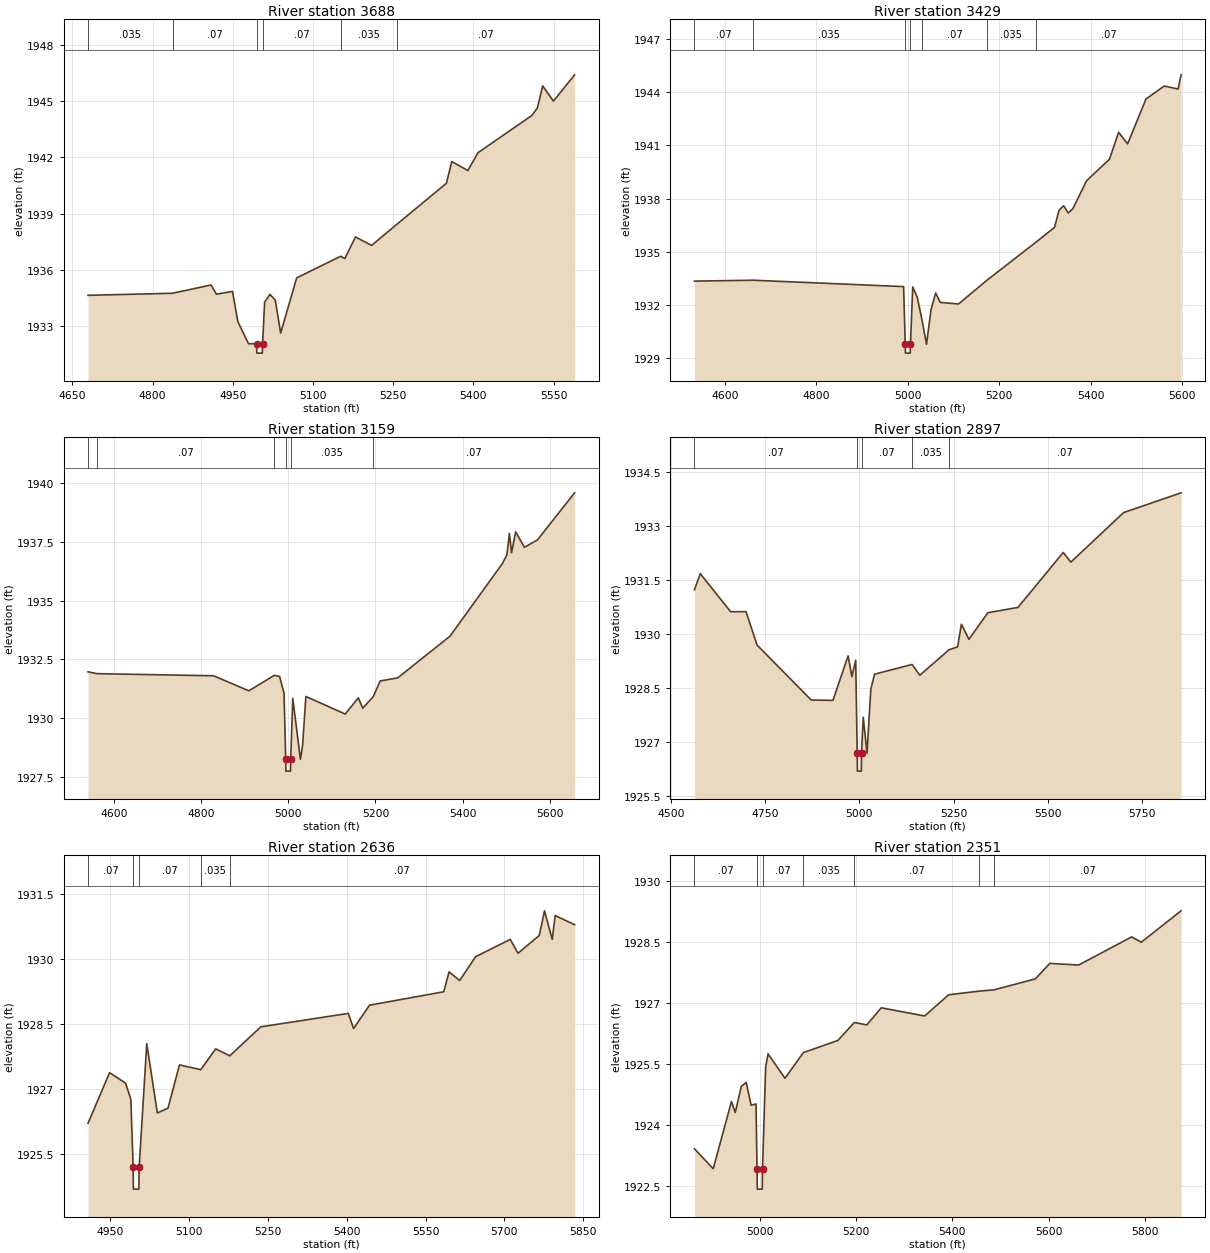
Type RM Length L Ch R = 1,3688,259,259,259
BEGIN DESCRIPTION:
Little Elm Creek A 3687.686
END DESCRIPTION:
XS GIS Cut Line= 3
      1528925.90      6810457.75      1528906.26      6810137.45
      1528925.88      6809548.38
#Sta/Elev= 30
  4679.1 1934.64  4837.2 1934.75  4909.3 1935.19  4919.3 1934.70  4949.4 1934.85
  4959.4 1933.24  4979.4 1932.06  4994.4 1932.06  4994.9 1931.56  5005.2 1931.56
  5005.7 1932.06  5009.5 1934.27  5019.5 1934.69  5029.5 1934.38  5039.5 1932.63
  5069.5 1935.57  5151.7 1936.72  5159.5 1936.60  5179.5 1937.75  5209.6 1937.30
  5257.5 1938.44  5349.6 1940.61  5359.6 1941.77  5389.7 1941.29  5408.7 1942.24
  5509.7 1944.23  5519.7 1944.62  5529.7 1945.80  5549.8 1944.99  5589.4 1946.39
#Mann=6,-1,0
  4679.1   0.035       0  4837.2    0.07       0  4994.4    0.07       0
  5005.7    0.07       0  5151.7   0.035       0  5257.5    0.07       0
Bank Sta=4994.4,5005.7
Exp/Cntr=0.3,0.1

Type RM Length L Ch R = 1,3429,270,270,270
BEGIN DESCRIPTION:
Little Elm Creek A 3429.132
END DESCRIPTION:
XS GIS Cut Line= 3
      1529137.18      6810655.53      1529134.01      6810188.74
      1529153.69      6809591.36
#Sta/Elev= 30
  4533.2 1933.35  4662.3 1933.40  4990.7 1933.04  4994.3 1929.79  4994.8 1929.29
  5005.2 1929.29  5005.7 1929.79  5010.7 1933.02  5020.8 1932.42  5031.4 1931.10
  5040.8 1929.79  5050.8 1931.75  5060.8 1932.68  5070.8 1932.15  5110.8 1932.06
  5173.6 1933.41  5279.5 1935.53  5320.9 1936.38  5330.9 1937.35  5340.9 1937.60
  5350.9 1937.19  5360.9 1937.43  5391.0 1939.01  5441.0 1940.22  5461.0 1941.74
  5480.8 1941.09  5521.0 1943.62  5561.0 1944.35  5591.1 1944.18  5597.7 1944.98
#Mann=7,-1,0
  4533.2    0.07       0  4662.3   0.035       0  4994.3   0.035       0
  5005.7   0.035       0  5031.4    0.07       0  5173.6   0.035       0
  5279.5    0.07       0
Bank Sta=4994.3,5005.7
Exp/Cntr=0.3,0.1

Type RM Length L Ch R = 1,3159,262,262,262
BEGIN DESCRIPTION:
Little Elm Creek A 3159.445
END DESCRIPTION:
XS GIS Cut Line= 3
      1529330.65      6810693.85      1529388.09      6810238.46
      1529429.35      6809583.16
#Sta/Elev= 30
  4541.0 1931.97  4561.7 1931.89  4829.1 1931.80  4909.7 1931.16  4968.3 1931.82
  4980.3 1931.77  4990.4 1931.06  4994.3 1928.24  4994.8 1927.74  5005.2 1927.74
  5005.7 1928.24  5010.5 1930.84  5028.0 1928.24  5033.0 1928.84  5040.5 1930.92
  5130.7 1930.17  5160.8 1930.86  5170.8 1930.42  5194.9 1930.91  5210.9 1931.58
  5251.0 1931.71  5371.2 1933.49  5491.4 1936.59  5501.5 1936.96  5507.1 1937.86
  5512.1 1937.04  5521.5 1937.93  5541.5 1937.27  5571.6 1937.59  5656.6 1939.59
#Mann=6,-1,0
  4541.0   0.035       0  4561.7    0.07       0  4968.3   0.035       0
  4994.3   0.035       0  5005.7   0.035       0  5194.9    0.07       0
Bank Sta=4994.3,5005.7
Exp/Cntr=0.3,0.1

Type RM Length L Ch R = 1,2897,261,261,261
BEGIN DESCRIPTION:
Little Elm Creek A 2896.987
END DESCRIPTION:
XS GIS Cut Line= 3
      1529584.84      6810723.26      1529634.87      6810288.32
      1529689.11      6809435.85
#Sta/Elev= 30
  4562.2 1931.23  4577.6 1931.68  4658.1 1930.62  4699.1 1930.62  4728.5 1929.69
  4872.2 1928.16  4929.9 1928.15  4970.1 1929.39  4980.2 1928.81  4990.3 1929.27
  4994.3 1926.68  4994.8 1926.18  5005.2 1926.18  5005.7 1926.68  5010.3 1927.68
  5020.4 1926.68  5030.4 1928.46  5040.4 1928.88  5140.1 1929.15  5160.6 1928.85
  5238.1 1929.56  5260.9 1929.64  5270.9 1930.27  5290.9 1929.85  5341.0 1930.59
  5421.2 1930.74  5541.4 1932.27  5561.5 1932.00  5701.7 1933.38  5854.2 1933.93
#Mann=5,-1,0
  4562.2    0.07       0  4994.3    0.07       0  5005.7    0.07       0
  5140.1   0.035       0  5238.1    0.07       0
Bank Sta=4994.3,5005.7
Exp/Cntr=0.3,0.1

Type RM Length L Ch R = 1,2636,285,285,285
BEGIN DESCRIPTION:
Little Elm Creek A 2636.354
END DESCRIPTION:
XS GIS Cut Line= 3
      1529867.67      6810428.67      1529880.00      6810338.00
      1529985.43      6809511.30
#Sta/Elev= 30
  4908.5 1926.21  4949.5 1927.38  4979.8 1927.14  4989.9 1926.77  4994.3 1925.19
  4994.8 1924.69  5005.2 1924.69  5005.7 1925.19  5020.2 1928.05  5040.3 1926.45
  5060.5 1926.56  5082.4 1927.56  5122.8 1927.45  5151.2 1927.93  5178.0 1927.77
  5237.0 1928.44  5403.2 1928.75  5413.3 1928.40  5443.6 1928.94  5584.7 1929.25
  5594.8 1929.71  5614.9 1929.51  5645.2 1930.06  5711.1 1930.46  5725.8 1930.14
  5766.2 1930.55  5776.2 1931.12  5790.9 1930.46  5796.4 1931.01  5833.4 1930.80
#Mann=5,-1,0
  4908.5    0.07       0  4994.3    0.07       0  5005.7    0.07       0
  5122.8   0.035       0  5178.0    0.07       0
Bank Sta=4994.3,5005.7
Exp/Cntr=0.3,0.1

Type RM Length L Ch R = 1,2351,266,266,266
BEGIN DESCRIPTION:
Little Elm Creek A 2351.273
END DESCRIPTION:
XS GIS Cut Line= 3
      1530122.76      6810523.43      1530149.47      6810390.39
      1530176.93      6809515.32
#Sta/Elev= 30
  4864.3 1923.42  4903.3 1922.93  4941.2 1924.58  4949.1 1924.31  4961.6 1924.95
  4971.8 1925.05  4982.0 1924.49  4992.2 1924.52  4994.3 1922.93  4994.8 1922.43
  5005.2 1922.43  5005.7 1922.93  5012.2 1925.42  5017.2 1925.75  5052.4 1925.15
  5090.6 1925.78  5162.5 1926.08  5196.5 1926.52  5222.5 1926.46  5252.5 1926.88
  5342.6 1926.68  5392.6 1927.20  5456.3 1927.29  5486.7 1927.32  5572.7 1927.59
  5602.7 1927.97  5662.7 1927.93  5772.8 1928.62  5792.8 1928.49  5875.5 1929.26
#Mann=7,-1,0
  4864.3    0.07       0  4994.3    0.07       0  5005.7    0.07       0
  5090.6   0.035       0  5196.5    0.07       0  5456.3   0.035       0
  5486.7    0.07       0
Bank Sta=4994.3,5005.7
Exp/Cntr=0.3,0.1