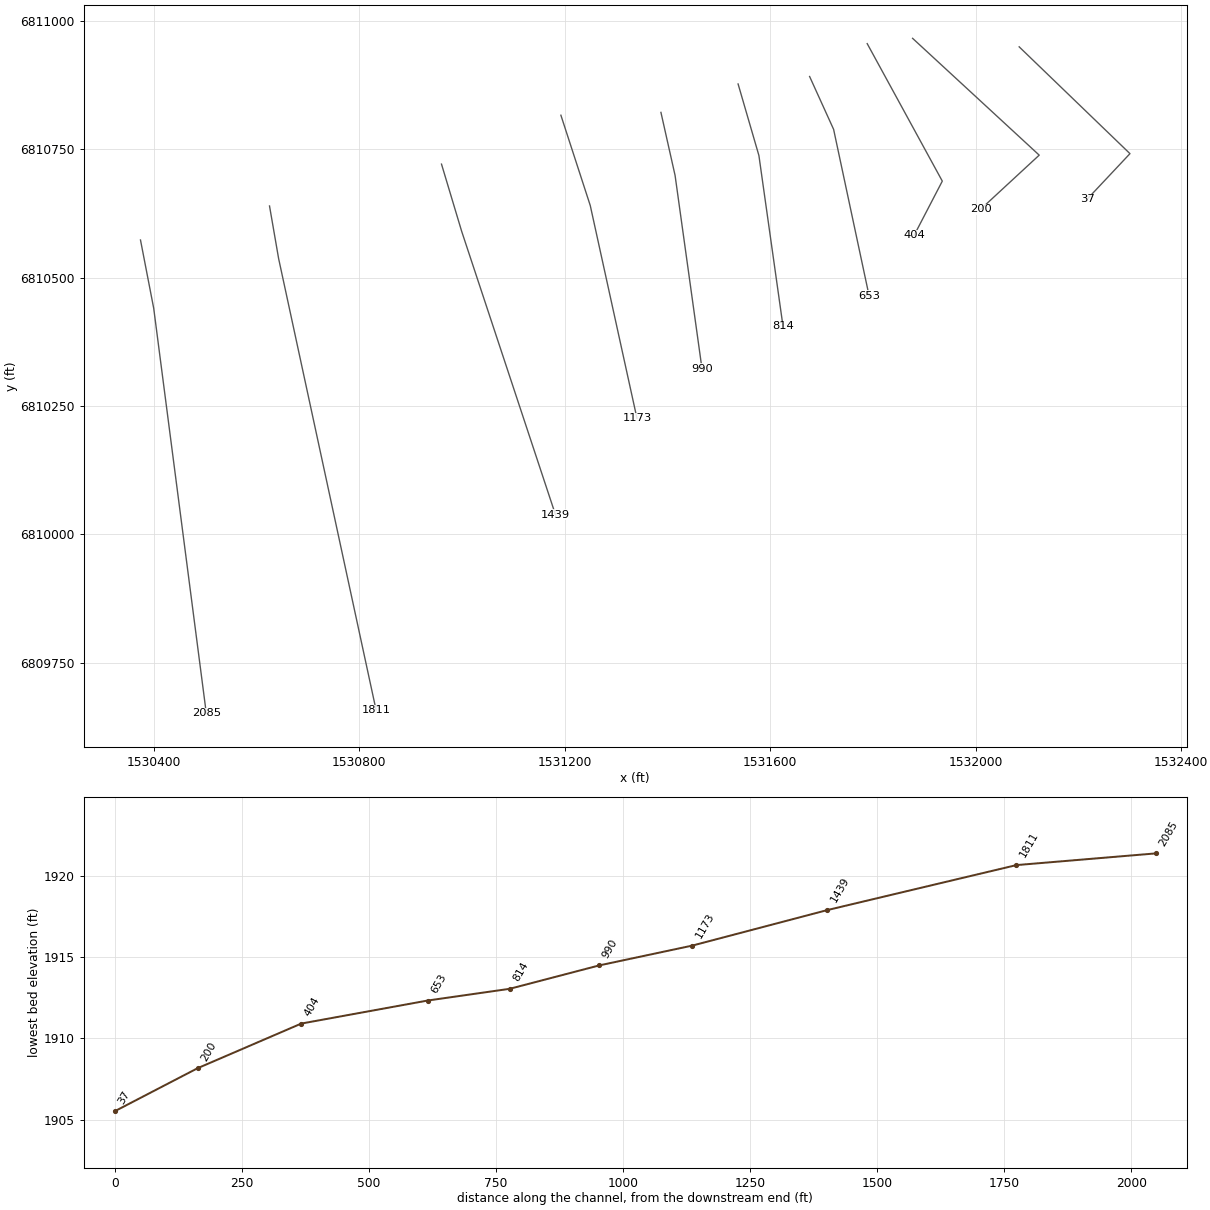
HEC-RAS study Little Elm Creek A.prj: Little Elm Creek A Base Level Engineering

--- Little Elm Creek A.g01 (geometry) --- (continued)

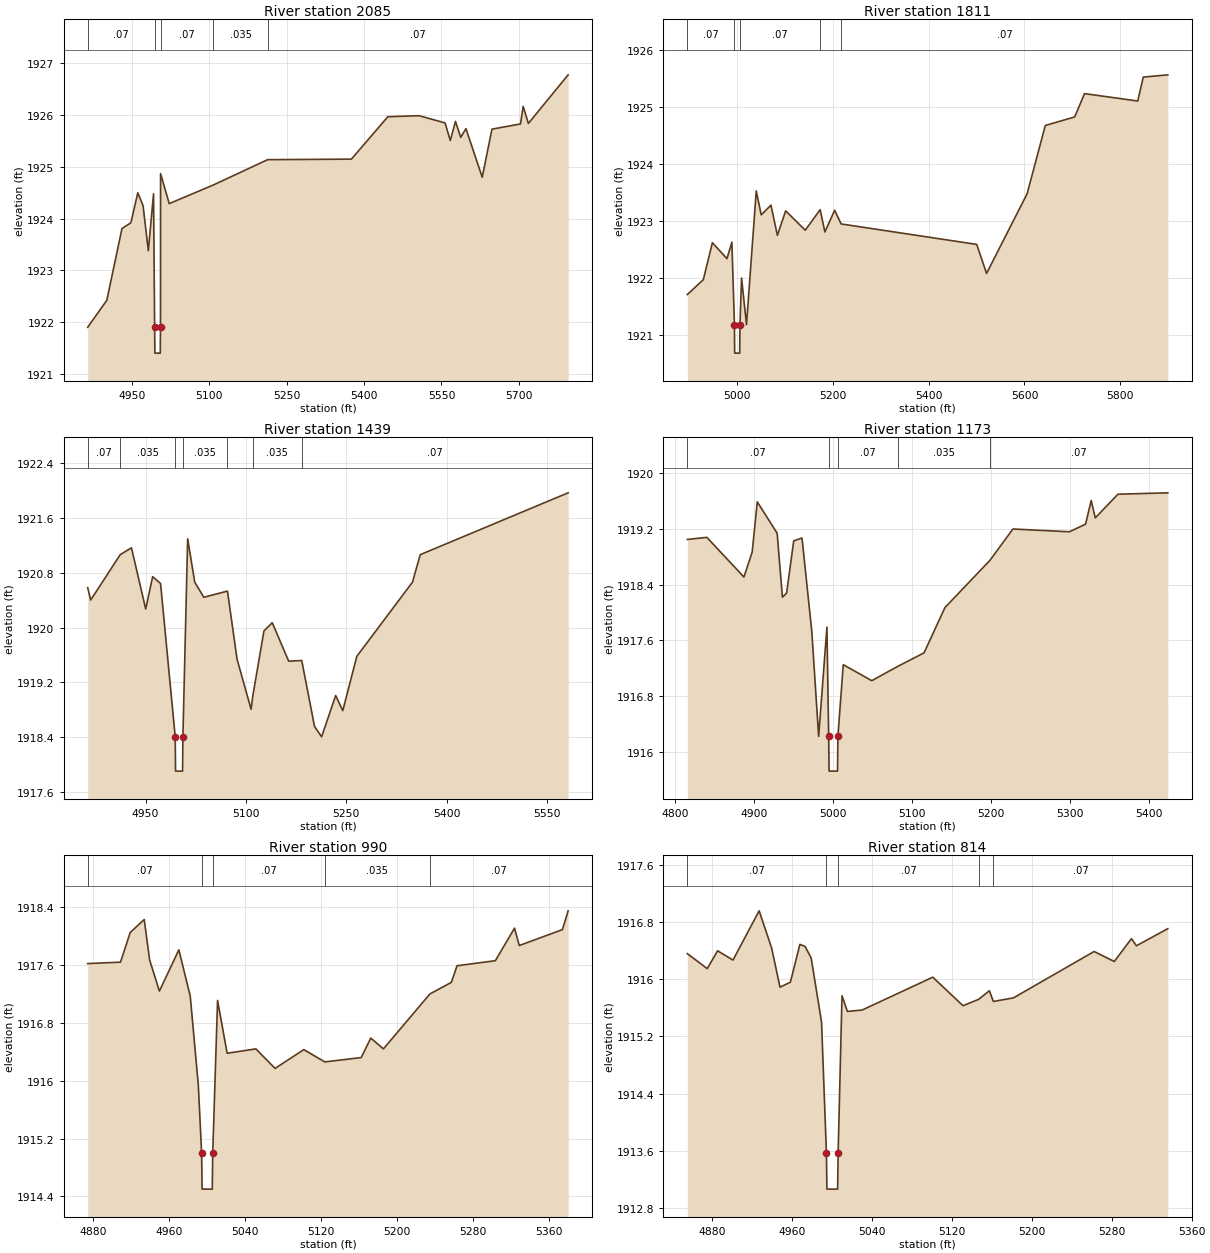
Type RM Length L Ch R = 1,2085,274,274,274
BEGIN DESCRIPTION:
Little Elm Creek A 2085.479
END DESCRIPTION:
XS GIS Cut Line= 3
      1530373.75      6810573.31      1530399.47      6810440.38
      1530501.90      6809651.60
#Sta/Elev= 30
  4864.6 1921.90  4901.6 1922.42  4931.1 1923.81  4948.3 1923.92  4961.7 1924.50
  4971.9 1924.25  4982.1 1923.38  4992.2 1924.48  4994.3 1921.90  4994.8 1921.40
  5005.2 1921.40  5005.7 1921.90  5005.8 1924.87  5022.6 1924.29  5107.9 1924.65
  5213.3 1925.14  5375.5 1925.15  5446.1 1925.97  5506.6 1925.99  5557.0 1925.85
  5567.1 1925.51  5577.2 1925.88  5587.3 1925.57  5597.4 1925.74  5629.0 1924.80
  5647.8 1925.73  5703.1 1925.83  5708.3 1926.17  5718.4 1925.84  5795.4 1926.78
#Mann=5,-1,0
  4864.6    0.07       0  4994.3    0.07       0  5005.7    0.07       0
  5107.9   0.035       0  5213.3    0.07       0
Bank Sta=4994.3,5005.7
Exp/Cntr=0.3,0.1

Type RM Length L Ch R = 1,1811,372,372,372
BEGIN DESCRIPTION:
Little Elm Creek A 1811.284
END DESCRIPTION:
XS GIS Cut Line= 3
      1530624.97      6810639.50      1530642.71      6810537.03
      1530832.48      6809657.98
#Sta/Elev= 30
  4896.0 1921.71  4929.3 1921.97  4948.3 1922.62  4978.7 1922.34  4989.0 1922.63
  4994.3 1921.18  4994.8 1920.68  5005.3 1920.68  5005.8 1921.18  5009.2 1922.00
  5019.5 1921.18  5039.9 1923.53  5050.2 1923.11  5070.6 1923.28  5084.0 1922.75
  5101.3 1923.18  5142.2 1922.84  5173.3 1923.20  5183.2 1922.81  5203.6 1923.19
  5217.1 1922.95  5500.3 1922.59  5520.8 1922.08  5605.5 1923.48  5643.5 1924.68
  5704.9 1924.83  5725.4 1925.24  5836.5 1925.11  5848.1 1925.53  5899.3 1925.57
#Mann=5,-1,0
  4896.0    0.07       0  4994.3    0.07       0  5005.8    0.07       0
  5173.3   0.035       0  5217.1    0.07       0
Bank Sta=4994.3,5005.8
Exp/Cntr=0.3,0.1

Type RM Length L Ch R = 1,1439,266,266,266
BEGIN DESCRIPTION:
Little Elm Creek A 1439.214
END DESCRIPTION:
XS GIS Cut Line= 3
      1530959.83      6810721.01      1530999.06      6810590.27
      1531181.80      6810038.23
#Sta/Elev= 30
  4863.5 1920.58  4868.0 1920.40  4912.1 1921.06  4928.9 1921.16  4950.2 1920.27
  4960.6 1920.74  4972.4 1920.64  4994.3 1918.41  4994.8 1917.91  5005.3 1917.91
  5005.8 1918.41  5012.9 1921.29  5023.5 1920.66  5037.0 1920.44  5072.4 1920.53
  5086.7 1919.54  5107.7 1918.81  5110.2 1919.00  5126.9 1919.95  5139.3 1920.07
  5163.9 1919.51  5183.4 1919.52  5202.5 1918.56  5213.1 1918.41  5234.1 1919.01
  5244.7 1918.79  5265.7 1919.58  5348.9 1920.66  5360.5 1921.06  5581.5 1921.96
#Mann=7,-1,0
  4863.5    0.07       0  4912.1   0.035       0  4994.3   0.035       0
  5005.8   0.035       0  5072.4    0.07       0  5110.2   0.035       0
  5183.4    0.07       0
Bank Sta=4994.3,5005.8
Exp/Cntr=0.3,0.1

Type RM Length L Ch R = 1,1173,183,183,183
BEGIN DESCRIPTION:
Little Elm Creek A 1173.125
END DESCRIPTION:
XS GIS Cut Line= 3
      1531192.29      6810816.21      1531249.47      6810640.38
      1531340.38      6810226.24
#Sta/Elev= 30
  4815.1 1919.05  4839.8 1919.08  4886.8 1918.51  4897.3 1918.87  4903.7 1919.59
  4928.9 1919.14  4935.6 1918.22  4940.9 1918.28  4949.9 1919.03  4960.4 1919.07
  4972.8 1917.73  4981.5 1916.22  4992.0 1917.79  4994.2 1916.22  4994.7 1915.72
  5005.4 1915.72  5005.9 1916.22  5012.7 1917.25  5048.8 1917.02  5082.5 1917.23
  5115.1 1917.42  5141.5 1918.07  5198.6 1918.75  5227.7 1919.20  5299.3 1919.16
  5319.8 1919.27  5326.9 1919.61  5332.1 1919.36  5360.8 1919.70  5424.0 1919.72
#Mann=5,-1,0
  4815.1    0.07       0  4994.2    0.07       0  5005.9    0.07       0
  5082.5   0.035       0  5198.6    0.07       0
Bank Sta=4994.2,5005.9
Exp/Cntr=0.3,0.1

Type RM Length L Ch R = 1,990,176,176,176
BEGIN DESCRIPTION:
Little Elm Creek A 990.296
END DESCRIPTION:
XS GIS Cut Line= 3
      1531387.07      6810821.74      1531414.63      6810698.89
      1531467.10      6810322.03
#Sta/Elev= 30
  4874.1 1917.62  4908.7 1917.64  4918.9 1918.05  4933.7 1918.23  4939.4 1917.67
  4949.7 1917.24  4970.2 1917.81  4982.2 1917.17  4990.7 1915.94  4994.2 1915.00
  4994.7 1914.50  5005.4 1914.50  5005.9 1915.00  5011.0 1917.11  5021.1 1916.38
  5051.4 1916.44  5071.6 1916.17  5101.9 1916.43  5124.0 1916.26  5162.4 1916.32
  5172.5 1916.59  5185.8 1916.44  5234.8 1917.20  5257.4 1917.36  5263.4 1917.59
  5303.8 1917.66  5324.0 1918.11  5329.0 1917.87  5374.5 1918.09  5380.5 1918.35
#Mann=5,-1,0
  4874.1    0.07       0  4994.2    0.07       0  5005.9    0.07       0
  5124.0   0.035       0  5234.8    0.07       0
Bank Sta=4994.2,5005.9
Exp/Cntr=0.3,0.1

Type RM Length L Ch R = 1,814,161,161,161
BEGIN DESCRIPTION:
Little Elm Creek A 813.799
END DESCRIPTION:
XS GIS Cut Line= 3
      1531537.30      6810877.07      1531577.83      6810737.74
      1531624.81      6810404.94
#Sta/Elev= 30
  4854.9 1916.36  4874.8 1916.15  4885.2 1916.40  4900.6 1916.27  4926.8 1916.96
  4939.3 1916.44  4947.7 1915.89  4958.1 1915.96  4967.6 1916.49  4972.8 1916.46
  4978.9 1916.30  4989.3 1915.40  4994.2 1913.56  4994.7 1913.06  5005.4 1913.06
  5005.9 1913.56  5009.8 1915.77  5015.2 1915.55  5030.0 1915.57  5100.7 1916.03
  5131.0 1915.63  5146.7 1915.72  5157.4 1915.84  5161.4 1915.69  5181.5 1915.74
  5262.3 1916.39  5282.5 1916.25  5299.7 1916.57  5304.7 1916.47  5336.1 1916.71
#Mann=5,-1,0
  4854.9    0.07       0  4994.2    0.07       0  5005.9    0.07       0
  5146.7   0.035       0  5161.4    0.07       0
Bank Sta=4994.2,5005.9
Exp/Cntr=0.3,0.1

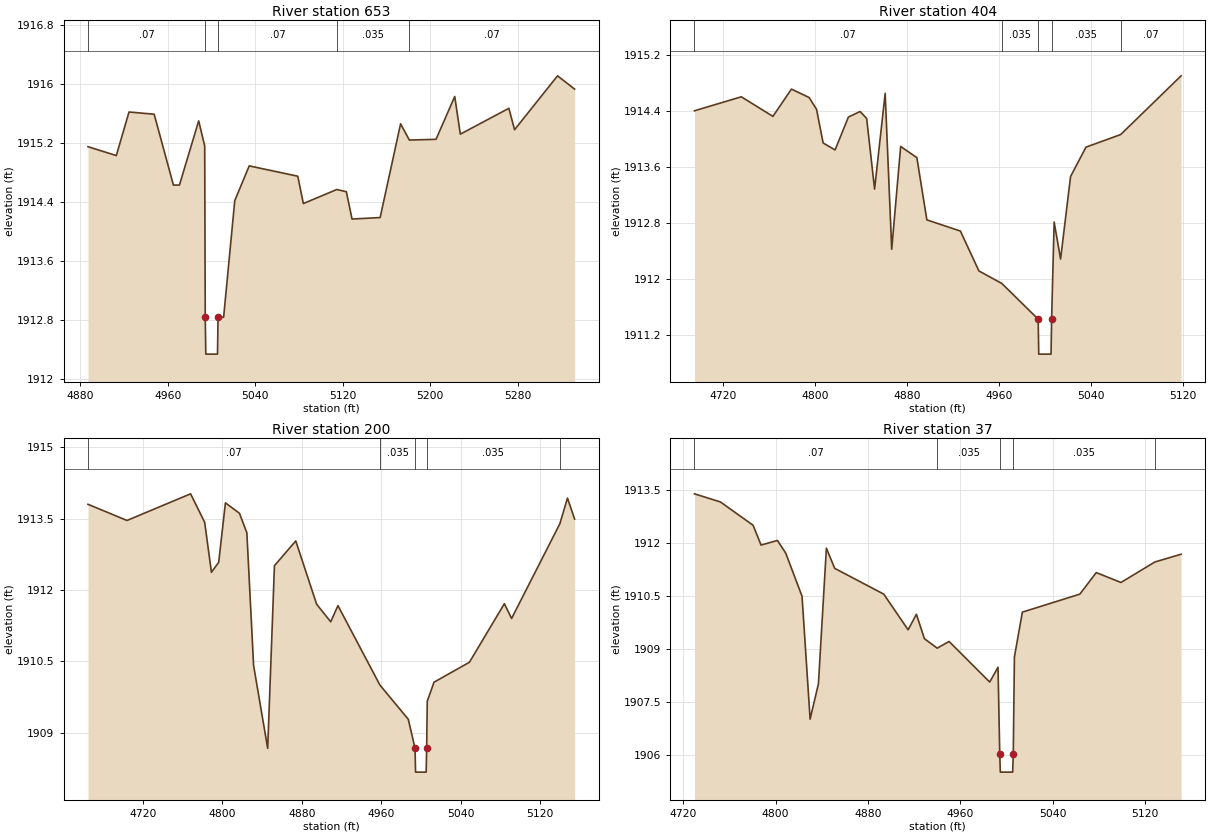
Type RM Length L Ch R = 1,653,249,249,249
BEGIN DESCRIPTION:
Little Elm Creek A 652.59
END DESCRIPTION:
XS GIS Cut Line= 3
      1531676.55      6810891.60      1531723.27      6810788.71
      1531792.49      6810464.11
#Sta/Elev= 30
  4887.0 1915.15  4912.9 1915.03  4924.5 1915.62  4947.5 1915.59  4965.1 1914.63
  4970.6 1914.63  4988.2 1915.50  4993.7 1915.16  4994.2 1912.84  4994.7 1912.34
  5005.4 1912.34  5005.9 1912.84  5011.0 1912.84  5021.2 1914.42  5034.4 1914.89
  5078.8 1914.75  5083.9 1914.38  5114.5 1914.57  5123.2 1914.54  5128.4 1914.17
  5154.1 1914.19  5172.8 1915.46  5180.8 1915.24  5205.2 1915.25  5222.3 1915.83
  5227.4 1915.32  5271.8 1915.67  5277.0 1915.38  5316.3 1916.11  5331.9 1915.93
#Mann=5,-1,0
  4887.0    0.07       0  4994.2    0.07       0  5005.9    0.07       0
  5114.5   0.035       0  5180.8    0.07       0
Bank Sta=4994.2,5005.9
Exp/Cntr=0.3,0.1

Type RM Length L Ch R = 1,404,204,204,204
BEGIN DESCRIPTION:
Little Elm Creek A 404.183
END DESCRIPTION:
XS GIS Cut Line= 3
      1531788.69      6810955.57      1531934.90      6810687.90
      1531880.21      6810582.66
#Sta/Elev= 30
  4695.0 1914.40  4735.8 1914.60  4763.3 1914.32  4779.4 1914.71  4794.8 1914.59
  4801.3 1914.42  4807.0 1913.94  4817.4 1913.84  4829.0 1914.31  4839.2 1914.39
  4844.9 1914.29  4851.8 1913.28  4861.0 1914.65  4866.7 1912.42  4874.5 1913.89
  4888.6 1913.73  4897.3 1912.84  4926.5 1912.68  4942.6 1912.11  4962.6 1911.93
  4994.2 1911.42  4994.7 1910.92  5005.4 1910.92  5005.9 1911.42  5008.1 1912.81
  5013.7 1912.28  5022.4 1913.46  5035.8 1913.88  5066.0 1914.06  5118.6 1914.90
#Mann=5,-1,0
  4695.0    0.07       0  4962.6   0.035       0  4994.2   0.035       0
  5005.9   0.035       0  5066.0    0.07       0
Bank Sta=4994.2,5005.9
Exp/Cntr=0.3,0.1

Type RM Length L Ch R = 1,200,163,163,163
BEGIN DESCRIPTION:
Little Elm Creek A 199.886
END DESCRIPTION:
XS GIS Cut Line= 3
      1531877.07      6810965.92      1532123.58      6810738.49
      1532009.75      6810633.29
#Sta/Elev= 30
  4664.6 1913.80  4703.9 1913.46  4768.0 1914.02  4782.2 1913.42  4789.0 1912.37
  4796.3 1912.58  4803.1 1913.83  4817.3 1913.61  4824.7 1913.20  4831.5 1910.41
  4845.7 1908.67  4852.5 1912.51  4874.0 1913.03  4895.0 1911.70  4909.2 1911.33
  4916.5 1911.67  4958.8 1910.00  4987.4 1909.28  4994.2 1908.67  4994.7 1908.17
  5005.4 1908.17  5005.9 1908.67  5006.5 1909.66  5013.3 1910.06  5049.0 1910.48
  5084.2 1911.71  5091.5 1911.40  5140.1 1913.39  5147.8 1913.93  5155.0 1913.49
#Mann=5,-1,0
  4664.6    0.07       0  4958.8   0.035       0  4994.2   0.035       0
  5005.9   0.035       0  5140.1    0.07       0
Bank Sta=4994.2,5005.9
Exp/Cntr=0.3,0.1

Type RM Length L Ch R = 1,37,0,0,0
BEGIN DESCRIPTION:
Little Elm Creek A 0.1
END DESCRIPTION:
XS GIS Cut Line= 3
      1532084.58      6810949.36      1532300.28      6810741.40
      1532216.73      6810652.54
#Sta/Elev= 30
  4729.7 1913.40  4752.2 1913.17  4780.5 1912.51  4787.4 1911.95  4801.6 1912.08
  4808.8 1911.72  4822.9 1910.50  4829.9 1907.02  4837.1 1908.02  4844.0 1911.86
  4851.2 1911.29  4893.7 1910.56  4914.8 1909.55  4922.0 1909.99  4928.9 1909.30
  4940.0 1909.03  4950.3 1909.22  4985.5 1908.07  4992.7 1908.49  4994.2 1906.02
  4994.7 1905.52  5005.4 1905.52  5005.9 1906.02  5006.9 1908.78  5013.8 1910.05
  5063.6 1910.56  5077.8 1911.17  5099.2 1910.89  5128.6 1911.47  5151.3 1911.69
#Mann=5,-1,0
  4729.7    0.07       0  4940.0   0.035       0  4994.2   0.035       0
  5005.9   0.035       0  5128.6    0.07       0
Bank Sta=4994.2,5005.9
Exp/Cntr=0.3,0.1

Chan Stop Cuts=-1