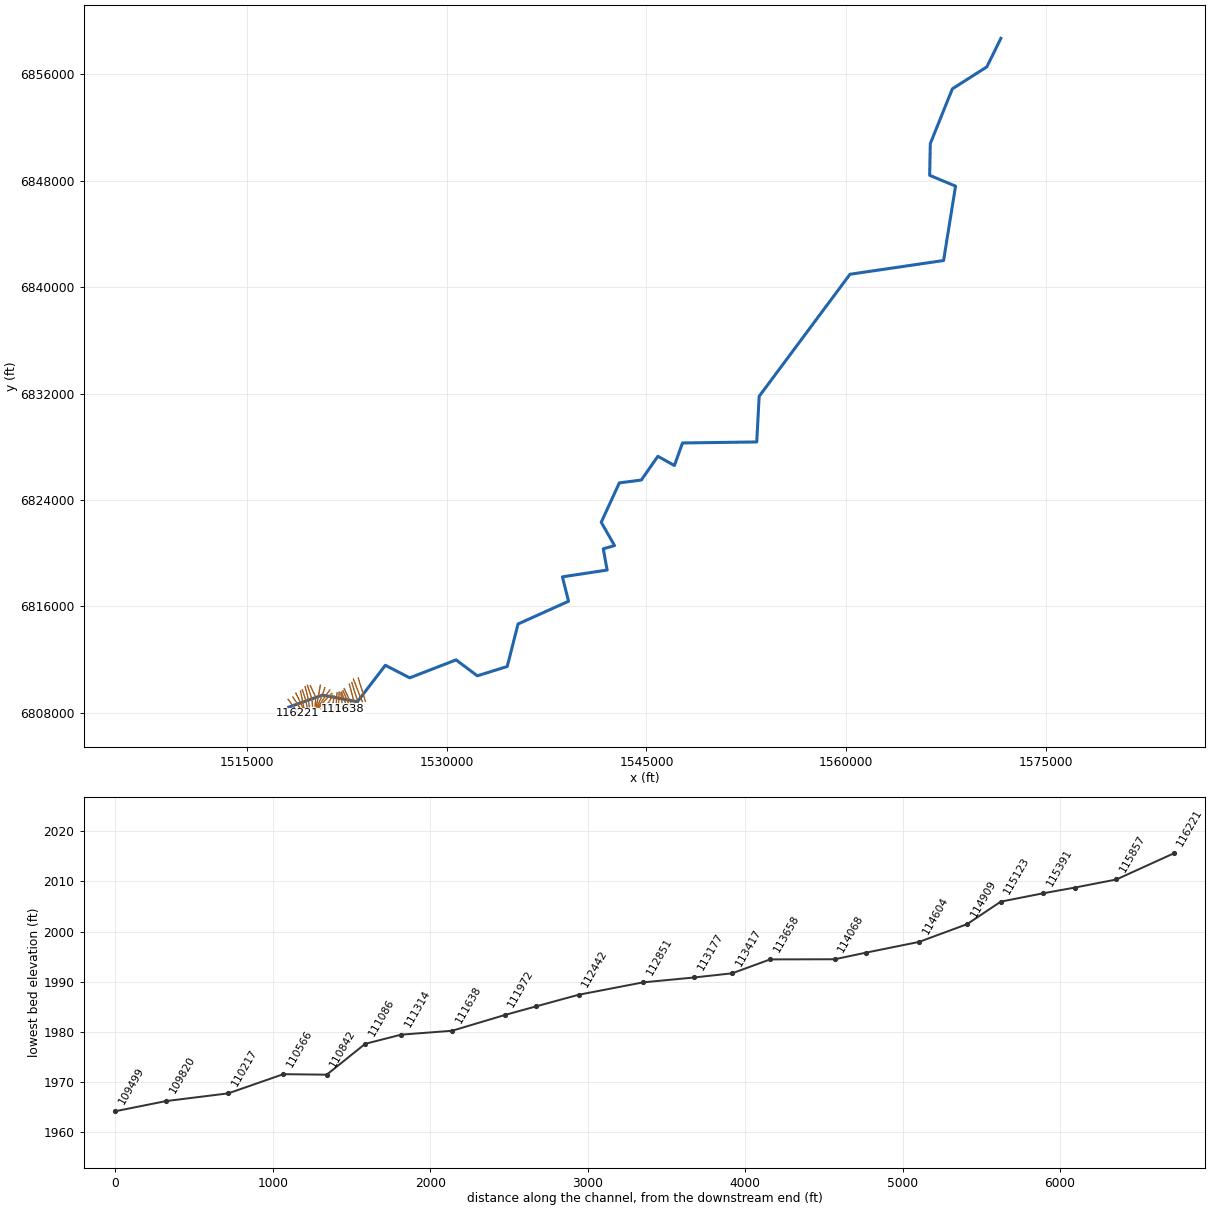
--- Little Elm Creek.prj (project) ---

Proj Title=Little Elm Creek Base Level Engineering
Current Plan=p01
Default Exp/Contr=0.3,0.1
English Units
Geom File=g01
Flow File=f01
Plan File=p01
Y Axis Title=Elevation
X Axis Title(PF)=Main Channel Distance
X Axis Title(XS)=Station
BEGIN DESCRIPTION:
Little Elm Creek
END DESCRIPTION:
DSS Export Rating Curves= 0
DSS Export Rating Curve Sorted= 0
DSS Export Volume Flow Curves= 0
DXF OffsetX= 0
DXF OffsetY= 0
DXF ScaleX= 1
DXF ScaleY= 10

--- Little Elm Creek.p01 (plan) ---

Plan Title=Multiple Run
Program Version=4.10
Short Identifier=Multiple
Geom File=g01
Flow File=f01
Subcritical Flow
K Sum by GR= 0
Std Step Tol= 0.01
Critical Tol= 0.01
Num of Std Step Trials= 20
Max Error Tol= 0.3
Flow Tol Ratio= 0.001
Split Flow NTrial= 30
Split Flow Tol= 0.02
Split Flow Ratio= 0.02
Log Output Level= 0
Friction Slope Method= 1
Unsteady Friction Slope Method= 2
Unsteady Bridges Friction Slope Method= 1
Parabolic Critical Depth
Global Vel Dist= 1 , 1 , 1
Global Log Level= 0
CheckData=True
Encroach Param=-1 ,0,0, 0
BEGIN DESCRIPTION:
Multiple Run
END DESCRIPTION:
Computation Interval=1HOUR
Output Interval=1HOUR
Run HTab= 0
Run UNet= 0
Run PostProcess= 0
Run WQNet= 0
UNET Theta= 1
UNET Theta Warmup= 1
UNET ZTol= 0.02
UNET ZSATol= 0.05
UNET MxIter= 20
UNET MaxInSteps= 0
UNET DtIC= 0
UNET DtMin= 0
UNET MaxCRTS= 20
UNET WFStab= 2
UNET SFStab= 1
UNET WFX= 1
UNET SFX= 1
UNET DSS MLevel= 4
UNET DZMax Abort= 100
UNET Convert EG Bridges= 0
UNET Use Existing IB Tables=-1
UNET Froude Reduction=False
UNET Froude Limit= 1
UNET Froude Power= 10
UNET Time Slicing=0,0, 5
UNET Junction Losses=0
Instantaneous Interval=1HOUR
Write IC File= 0
Write IC File at Sim End=0
Echo Input=False
Echo Parameters=False
Echo Output=False
Write Detailed= 0
WQ AD Non Conservative
WQ ULTIMATE=-1
WQ Max Comp Step=1HOUR
WQ Output Interval=15MIN
WQ Output Selected Increments= 0
WQ Output face flow=0
WQ Output face velocity=0
WQ Output face area=0
WQ Output face dispersion=0
WQ Output cell volume=0
WQ Output cell surface area=0
WQ Output cell continuity=0
WQ Output cumulative cell continuity=0
WQ Output face conc=0
WQ Output face dconc_dx=0
WQ Output face courant=0
WQ Output face peclet=0
WQ Output face adv mass=0
WQ Output face disp mass=0
WQ Output cell mass=0
WQ Output cell source sink temp=0
WQ Output cell source sink nsm=0
WQ Output MaxMinRange=-1
WQ Daily Max Min Mean=-1
WQ Daily Range=0
WQ Daily Time=0
WQ Create Restart=0
WQ Fixed Restart=0
WQ System Summary=0
WQ Use Fixed Temperature=0
Sorting and Armoring Iterations= 10
XS Update Threshold= 0.02
Hydraulics Update Threshold= 0.02
Energy Slope Method= 1
Volume Change Method= 0
XS Weighting Method= 0
Number of US Weighted Cross Sections= 1
Number of DS Weighted Cross Sections= 1
Upstream XS Weight=0.25
Main XS Weight=0.5
Downstream XS Weight=0.25
Number of DS XS's Weighted with US Boundary= 1
Upstream Boundary Weight= 1
Weight of XSs Associated with US Boundary= 0
Number of US XS's Weighted with DS Boundary= 1
Downstream Boundary Weight= 0.5
Weight of XSs Associated with DS Boundary= 0.5
Sediment Output Level= 4
Mass or Volume Output= 0
Output Increment Type= 1
Profile and TS Output Increment= 10
XS Output Flag= 0
XS Output Increment= 10
Disregard all LS=0
Disregard all Conn=0
Disregard all Breaches=0
Disregard all Pumps=0

--- Little Elm Creek.f01 (steady flow) ---

Flow Title=Multiple
Number of Profiles=7
Profile Names=10-year,25-year,50-year,1pct_min,100-year,1pct_plu,500-year
River Rch & RM= Little Elm Creek,Reach-1,116221
     541     803    1030     826    1320    1820    2200
River Rch & RM= Little Elm Creek,Reach-1,113658
     695    1040    1350    1080    1730    2380    2910
River Rch & RM= Little Elm Creek,Reach-1,110566
     643     947    1210     963    1540    2120    2530
River Rch & RM= Little Elm Creek,Reach-1,102449
     864    1290    1660    1320    2120    2920    3520
River Rch & RM= Little Elm Creek,Reach-1,95855
    1640    2490    3250    2620    4200    5770    7110
River Rch & RM= Little Elm Creek,Reach-1,85745
    1690    2540    3290    2630    4210    5790    6970
River Rch & RM= Little Elm Creek,Reach-1,64217
    1830    2760    3580    2860    4580    6300    7530
River Rch & RM= Little Elm Creek,Reach-1,51573
    2060    3180    4170    3340    5350    7360    8810
River Rch & RM= Little Elm Creek,Reach-1,40759
    2270    3480    4540    3630    5820    8010    9600
Boundary for River Rch & Prof#=Little Elm Creek,Reach-1,1
Up Type=0
Dn Type=3
Dn Slope=0.0036
Boundary for River Rch & Prof#=Little Elm Creek,Reach-1,2
Up Type=0
Dn Type=3
Dn Slope=0.0036
Boundary for River Rch & Prof#=Little Elm Creek,Reach-1,3
Up Type=0
Dn Type=3
Dn Slope=0.0036
Boundary for River Rch & Prof#=Little Elm Creek,Reach-1,4
Up Type=0
Dn Type=3
Dn Slope=0.0036
Boundary for River Rch & Prof#=Little Elm Creek,Reach-1,5
Up Type=0
Dn Type=3
Dn Slope=0.0036
Boundary for River Rch & Prof#=Little Elm Creek,Reach-1,6
Up Type=0
Dn Type=3
Dn Slope=0.0036
Boundary for River Rch & Prof#=Little Elm Creek,Reach-1,7
Up Type=0
Dn Type=3
Dn Slope=0.0036

--- Little Elm Creek.g01 (geometry) ---

Geom Title=Existing Conditions
Program Version=4.10

River Reach=Little Elm Creek,Reach-1
Reach XY= 30
        1518155.        6808438.      1520675.02      6809337.96
      1523303.72      6808841.37      1525401.38      6811580.53
      1527230.19      6810637.51      1530710.93      6811985.76
        1532305.        6810788.      1534549.57      6811490.17
      1535360.09      6814682.98      1539151.57      6816389.57
      1538691.67      6818224.59      1542049.55      6818735.55
      1541756.61      6820331.98      1542604.96      6820574.23
      1541605.46      6822324.28      1542962.86      6825285.05
        1544615.      6825498.63      1545856.65       6827284.9
      1547096.39      6826590.96      1547706.46      6828284.46
      1553278.53      6828360.86      1553460.33      6831790.51
      1560278.18      6840961.71      1567302.82      6841993.45
      1568202.83      6847582.55      1566258.84      6848396.62
      1566306.22       6850777.5      1567963.14      6854894.06
      1570549.42      6856543.58        1571605.        6858688.

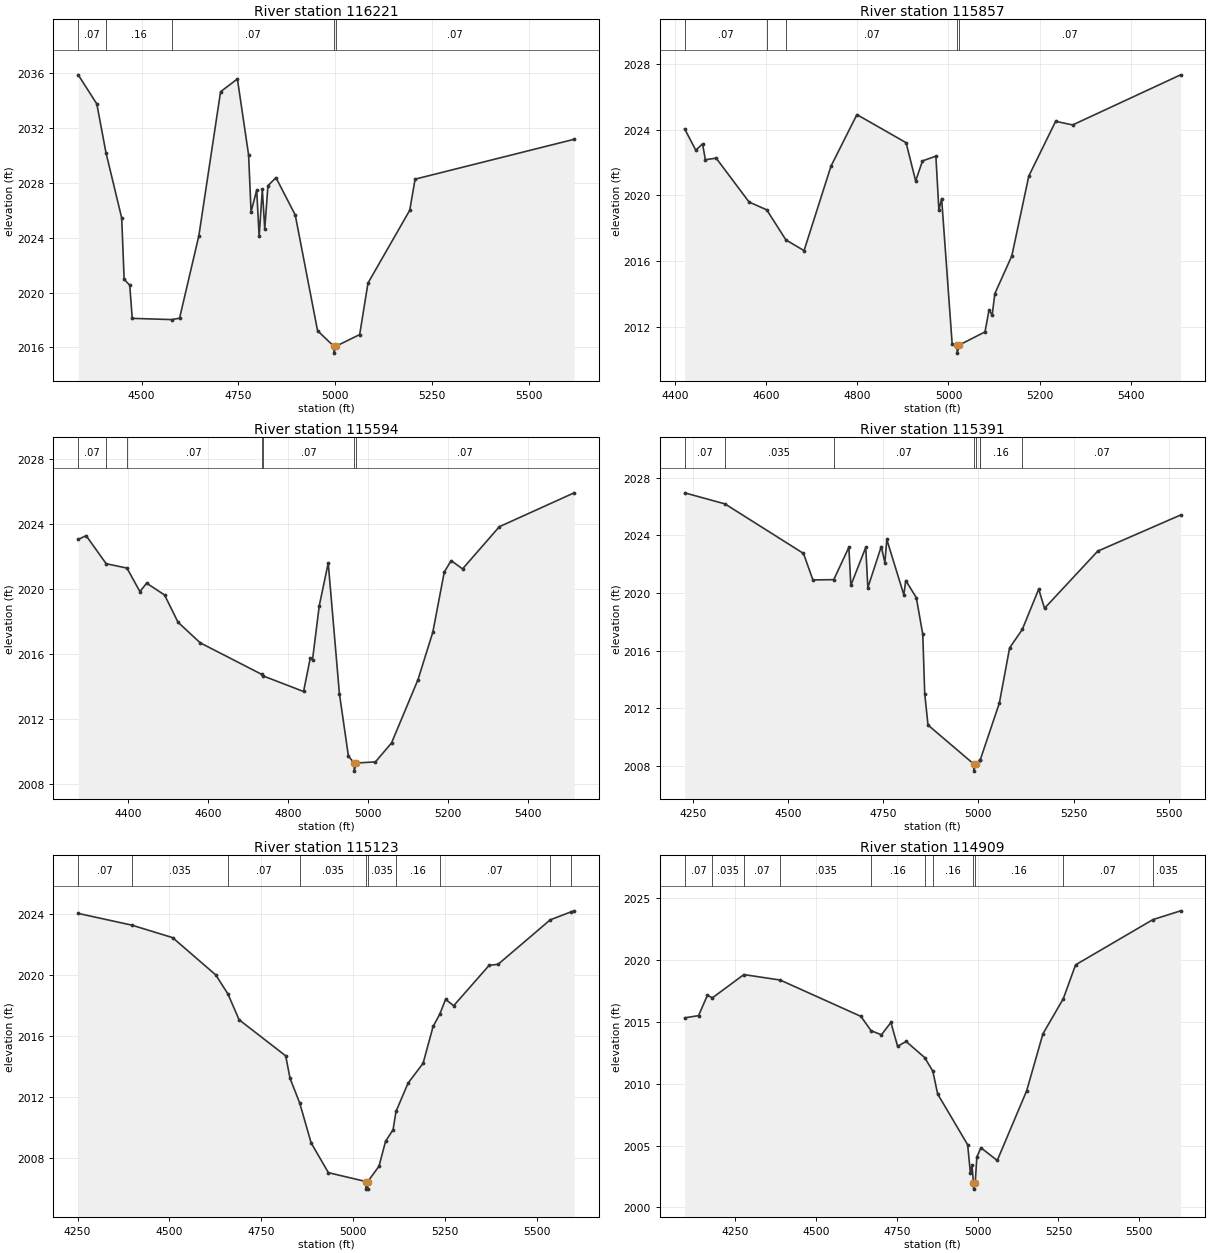
Type RM Length L Ch R = 1 ,116221  ,364,364,364
BEGIN DESCRIPTION:
Little Elm Creek 116221.209
END DESCRIPTION:
XS GIS Cut Line= 3
      1518098.45      6809018.22      1518503.28      6808492.16
      1518827.58       6807966.2
#Sta/Elev= 30
  4336.2 2035.84  4384.3 2033.72  4407.9 2030.18  4448.6 2025.42  4454.9 2020.96
  4469.4 2020.53  4475.8 2018.12  4577.6 2018.03  4598.1 2018.13    4648 2024.13
  4704.1 2034.61  4747.6 2035.54  4776.6    2030  4782.9 2025.88  4797.5 2027.45
  4803.8 2024.08    4812  2027.5  4818.3 2024.61  4826.5 2027.77  4847.3 2028.36
  4897.1 2025.64  4954.8 2017.22  4996.8 2016.09  4997.2 2015.59  5002.1 2016.09
  5063.6 2016.94  5085.1 2020.69  5192.9 2025.98  5206.9 2028.25  5617.9 2031.15
#Mann= 5 ,-1 , 0
  4336.2     .07       0  4407.9     .16       0  4577.6     .07       0
  4996.8     .07       0  5002.1     .07       0
Bank Sta=4996.8,5002.1
XS Rating Curve= 0 ,0
Exp/Cntr=0.3,0.1

Type RM Length L Ch R = 1 ,115857  ,263,263,263
BEGIN DESCRIPTION:
Little Elm Creek 115857.414
END DESCRIPTION:
XS GIS Cut Line= 3
      1518457.81      6809195.33      1518781.48      6808715.12
      1519035.92      6808273.48
#Sta/Elev= 30
  4420.9 2024.04  4445.3 2022.74  4460.2 2023.13  4466.3 2022.16    4490 2022.26
  4562.2 2019.59  4601.1 2019.11  4643.2 2017.28    4683 2016.63  4742.1 2021.77
    4799 2024.91    4907  2023.2    4928 2020.87    4943 2022.09  4972.4 2022.38
    4979 2019.09    4985  2019.8  5008.2 2010.93  5018.7 2010.89  5019.1 2010.39
    5024 2010.89  5080.2 2011.68    5089 2013.01    5096 2012.71  5101.8 2014.01
  5139.1 2016.31  5176.4 2021.17  5235.3  2024.5  5272.7 2024.28  5509.7 2027.33
#Mann= 5 ,-1 , 0
  4420.9     .07       0  4601.1     .16       0  4643.2     .07       0
  5018.7     .07       0    5024     .07       0
Bank Sta=5018.7,5024
XS Rating Curve= 0 ,0
Exp/Cntr=0.3,0.1

Type RM Length L Ch R = 1 ,115594  ,203,203,203
BEGIN DESCRIPTION:
Little Elm Creek 115593.765
END DESCRIPTION:
XS GIS Cut Line= 3
      1518681.76       6809481.8      1519002.71      6808832.15
      1519217.97      6808362.54
#Sta/Elev= 30
  4275.4 2023.07  4295.2  2023.3  4345.4 2021.57  4397.4  2021.3  4429.8 2019.85
  4446.7 2020.37  4491.6 2019.64  4525.2 2017.96  4580.8 2016.69  4734.4 2014.75
  4738.3 2014.65  4839.4 2013.69  4856.2 2015.75  4861.8 2015.65  4878.7 2018.98
  4901.1 2021.61  4929.1 2013.56  4951.6 2009.71  4965.8 2009.28  4966.2 2008.78
  4971.2 2009.28  5019.3 2009.35  5059.6 2010.52  5125.6 2014.41  5162.8 2017.34
  5191.6 2021.06  5208.8 2021.76  5237.3 2021.25  5329.3 2023.85  5516.6 2025.94
#Mann= 7 ,-1 , 0
  4275.4     .07       0  4345.4     .16       0  4397.4     .07       0
  4734.4    .035       0  4738.3     .07       0  4965.8     .07       0
  4971.2     .07       0
Bank Sta=4965.8,4971.2
XS Rating Curve= 0 ,0
Exp/Cntr=0.3,0.1

Type RM Length L Ch R = 1 ,115391  ,268,268,268
BEGIN DESCRIPTION:
Little Elm Creek 115390.869
END DESCRIPTION:
XS GIS Cut Line= 3
      1519030.72      6809643.25      1519189.78      6808888.53
      1519291.14      6808367.19
#Sta/Elev= 30
  4228.7 2026.96  4334.6 2026.19  4540.7 2022.75  4565.4 2020.91  4620.2 2020.93
  4659.9 2023.18    4665 2020.53  4704.2 2023.17  4709.7 2020.37    4745 2023.23
  4754.4 2022.11  4759.5 2023.72  4804.2 2019.88  4809.3 2020.87    4837 2019.68
    4854 2017.13  4859.1 2013.01  4867.7 2010.83  4987.6 2008.13    4988 2007.63
    4993 2008.13  5003.4 2008.37    5005 2008.42  5055.1 2012.36    5082 2016.19
  5115.3 2017.47  5158.4 2020.27  5173.7 2018.94  5313.4 2022.91  5531.1 2025.42
#Mann= 8 ,-1 , 0
  4228.7     .07       0  4334.6    .035       0  4620.2     .07       0
  4987.6     .07       0    4993     .07       0  5003.4    .035       0
    5005     .16       0  5115.3     .07       0
Bank Sta=4987.6,4993
XS Rating Curve= 0 ,0
Exp/Cntr=0.3,0.1

Type RM Length L Ch R = 1 ,115123  ,214,214,214
BEGIN DESCRIPTION:
Little Elm Creek 115122.932
END DESCRIPTION:
XS GIS Cut Line= 3
      1519166.14       6809742.2      1519406.72      6809033.84
      1519525.51      6808445.31
#Sta/Elev= 30
  4251.9 2024.07  4397.8  2023.3  4508.6 2022.48    4626 2020.03  4659.3 2018.77
  4689.3 2017.09  4816.1 2014.72  4827.8 2013.25  4854.2 2011.62  4885.3    2009
  4932.2 2007.05  5033.8 2006.47  5034.2 2005.97  5038.9 2005.97  5039.4 2006.47
  5069.7 2007.47  5087.6 2009.11    5108 2009.87    5116 2011.07  5148.8 2012.93
  5189.6 2014.23  5216.9 2016.65  5234.9 2017.45  5250.8 2018.43  5272.8 2018.01
  5369.2 2020.66  5393.6 2020.73  5535.4 2023.65  5591.7 2024.17  5600.4 2024.24
#Mann= 10 ,-1 , 0
  4251.9     .07       0  4397.8    .035       0  4659.3     .07       0
  4854.2    .035       0  5033.8    .035       0  5039.4    .035       0
    5116     .16       0  5234.9     .07       0  5535.4    .035       0
  5591.7     .07       0
Bank Sta=5033.8,5039.4
XS Rating Curve= 0 ,0
Exp/Cntr=0.3,0.1

Type RM Length L Ch R = 1 ,114909  ,305,305,305
BEGIN DESCRIPTION:
Little Elm Creek 114909.285
END DESCRIPTION:
XS GIS Cut Line= 3
      1519379.68      6809966.14       1519604.8      6809088.04
      1519692.18      6808466.15
#Sta/Elev= 30
  4093.5 2015.34  4136.5 2015.52  4163.8 2017.17  4179.3 2016.96  4276.6 2018.84
  4388.9  2018.4  4638.7 2015.46  4670.3  2014.3  4702.3 2013.97  4731.6 2014.97
  4752.3 2013.04  4778.7 2013.43  4835.9 2012.13  4861.3 2011.03  4876.2 2009.18
  4969.1 2005.07  4977.5 2002.79  4982.6 2003.41  4986.9 2001.98  4987.4 2001.48
  4992.5 2001.98  4997.4 2004.07  5010.1 2004.83  5060.6  2003.8  5151.5 2009.43
    5202 2014.05    5265 2016.89    5303 2019.63  5542.3 2023.29    5628    2024
#Mann= 11 ,-1 , 0
  4093.5     .07       0  4179.3    .035       0  4276.6     .07       0
  4388.9    .035       0  4670.3     .16       0  4835.9     .07       0
  4861.3     .16       0  4986.9     .07       0  4992.5     .16       0
    5265     .07       0  5542.3    .035       0
Bank Sta=4986.9,4992.5
XS Rating Curve= 0 ,0
Exp/Cntr=0.3,0.1

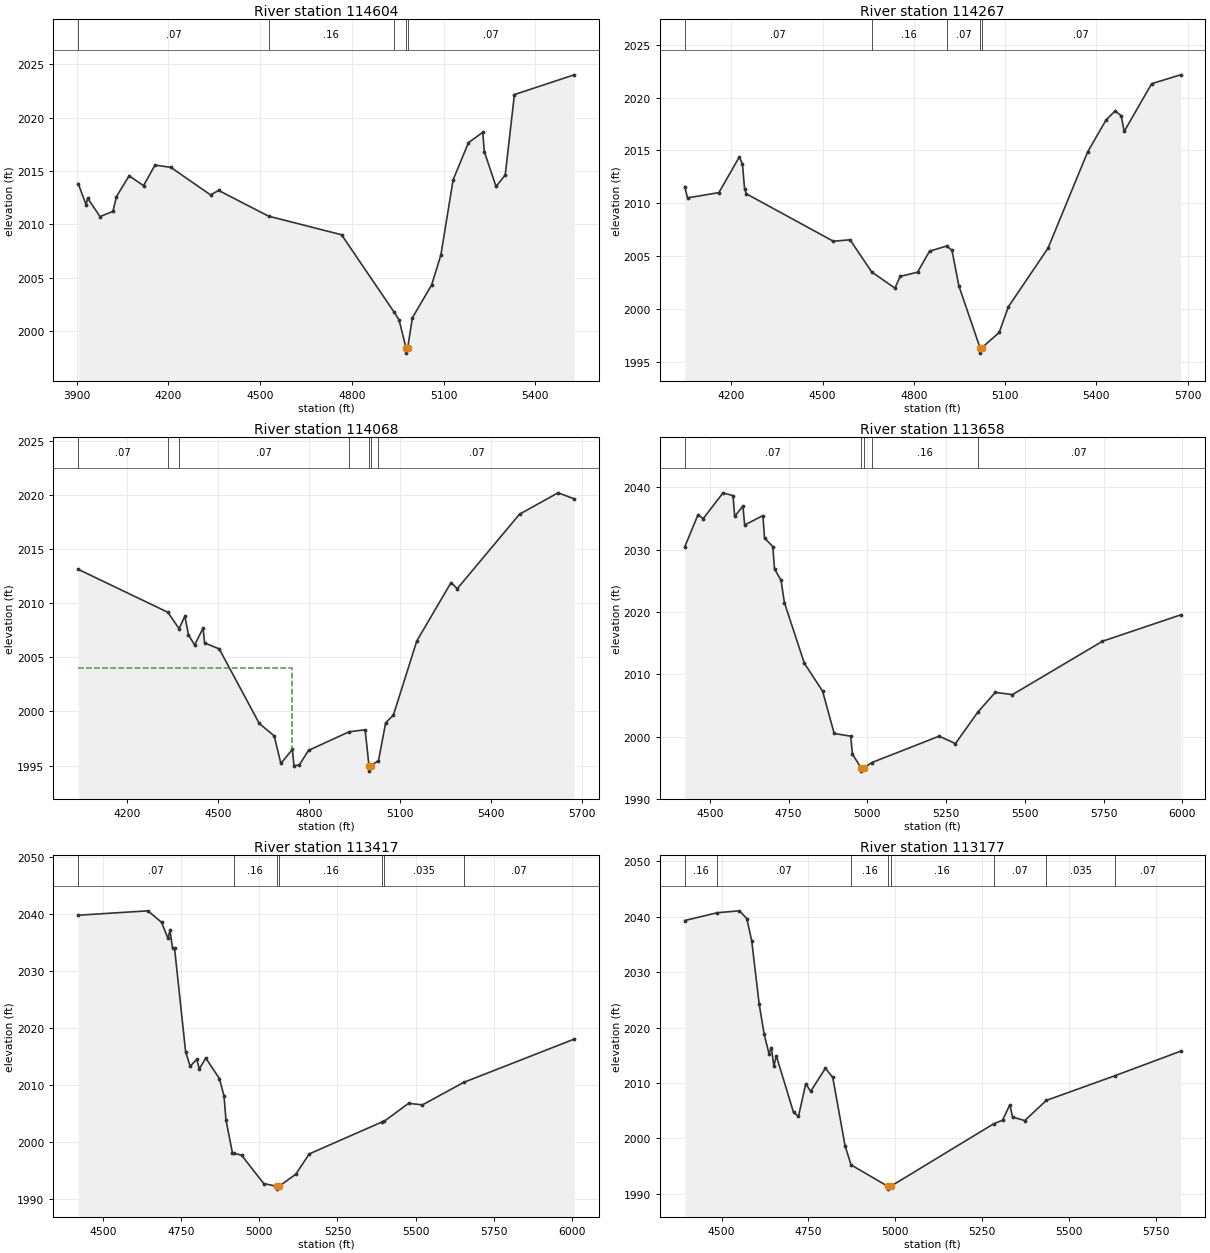
Type RM Length L Ch R = 1 ,114604  ,337,337,337
BEGIN DESCRIPTION:
Little Elm Creek 114603.85
END DESCRIPTION:
XS GIS Cut Line= 3
      1519541.13      6810075.55      1519894.52      6809038.93
        1519930.      6808513.03
#Sta/Elev= 30
  3904.8 2013.81  3930.5 2011.85  3935.7 2012.45  3976.2 2010.73  4018.4 2011.22
  4029.8  2012.6  4071.3 2014.55  4118.5 2013.63  4155.8 2015.55  4207.3 2015.35
  4337.9 2012.76    4364 2013.18  4527.4 2010.77  4766.2 2009.03  4938.2 2001.78
  4954.2 2001.06  4977.1 1998.44  4977.5 1997.94  4982.7 1998.44  4997.9 2001.25
  5061.1 2004.34  5091.1 2007.13  5131.2 2014.18  5181.3 2017.65  5228.2 2018.63
  5233.2 2016.82  5271.5 2013.55  5301.6 2014.62  5331.7 2022.16  5527.1 2024.01
#Mann= 5 ,-1 , 0
  3904.8     .07       0  4527.4     .16       0  4938.2     .07       0
  4977.1     .07       0  4982.7     .07       0
Bank Sta=4977.1,4982.7
XS Rating Curve= 0 ,0
Exp/Cntr=0.3,0.1

Type RM Length L Ch R = 1 ,114267  ,199,199,199
BEGIN DESCRIPTION:
Little Elm Creek 114267.342
END DESCRIPTION:
XS GIS Cut Line= 3
      1519765.07      6810049.55      1520173.33      6809188.43
        1520130.      6808513.01
#Sta/Elev= 30
    4047 2011.58  4056.4 2010.51  4159.4 2011.01  4226.6 2014.39  4236.9 2013.72
  4243.8 2011.38  4249.4  2010.9  4535.7  2006.4  4590.4 2006.54  4661.7 2003.49
  4737.9 2001.96  4755.1 2003.07  4812.3 2003.47  4851.6 2005.46  4908.3 2005.95
  4925.4 2005.54  4948.1 2002.17  5017.7  1996.3  5018.1  1995.8  5023.3  1996.3
  5080.6 1997.76  5110.7 2000.19  5240.9 2005.74  5371.2 2014.86  5431.3 2017.87
  5461.4 2018.75  5481.4  2018.3  5491.4 2016.81  5581.6 2021.33  5676.8 2022.17
#Mann= 5 ,-1 , 0
    4047     .07       0  4661.7     .16       0  4908.3     .07       0
  5017.7     .07       0  5023.3     .07       0
Bank Sta=5017.7,5023.3
XS Rating Curve= 0 ,0
Exp/Cntr=0.3,0.1

Type RM Length L Ch R = 1 ,114068  ,410,410,410
BEGIN DESCRIPTION:
Little Elm Creek 114067.858
END DESCRIPTION:
XS GIS Cut Line= 3
       1520520.3      6810085.99      1520357.17      6809138.94
      1520207.93      6808482.39
#Sta/Elev= 30
    4039 2013.16  4334.6 2009.18  4371.2 2007.67  4390.6 2008.82  4402.3 2007.11
  4422.6 2006.15  4450.5 2007.72  4455.6 2006.35  4503.7 2005.79  4635.7 1998.89
    4685 1997.74  4706.7 1995.19  4744.9 1996.49    4750 1994.98  4767.6 1995.05
    4798  1996.4  4931.4 1998.12  4984.5 1998.31  4997.2 1994.98  4997.7 1994.48
  5002.9 1994.98  5028.5 1995.45  5052.2 1998.96  5077.7 1999.67  5154.8 2006.53
  5267.6 2011.93  5288.1 2011.37  5493.2 2018.26  5620.1 2020.24  5673.3 2019.69
#Mann= 7 ,-1 , 0
    4039     .07       0  4334.6    .035       0  4371.2     .07       0
  4931.4     .16       0  4997.2     .07       0  5002.9     .07       0
  5028.5     .07       0
#XS Ineff= 2 , 0
       0    4744    2004               0
Permanent Ineff=
       F       F
Bank Sta=4997.2,5002.9
XS Rating Curve= 0 ,0
Exp/Cntr=0.3,0.1

Type RM Length L Ch R = 1 ,113658  ,241,241,241
BEGIN DESCRIPTION:
Little Elm Creek 113657.67
END DESCRIPTION:
XS GIS Cut Line= 3
      1520858.85      6809888.06      1520675.02      6809337.96
      1520265.82      6808431.33
#Sta/Elev= 30
    4420 2030.42  4462.2 2035.58  4478.8 2034.97  4541.9 2039.11  4573.5 2038.66
  4578.8 2035.34  4605.1 2036.98  4610.4 2033.95  4668.3 2035.45  4673.6 2031.85
  4699.9 2030.49  4705.2  2026.9  4725.8  2025.1  4736.8 2021.47  4799.9 2011.77
  4857.9 2007.28  4894.7  2000.5  4947.2 2000.05  4952.6 1997.19  4980.3 1994.95
  4980.8 1994.45  4988.1 1994.95  5014.1 1995.82  5227.9 2000.06  5279.7 1998.87
  5350.9 2003.93  5406.3 2007.09  5460.8 2006.73  5746.5 2015.29  5994.7 2019.52
#Mann= 5 ,-1 , 0
    4420     .07       0  4980.3     .07       0  4988.1     .07       0
  5014.1     .16       0  5350.9     .07       0
Bank Sta=4980.3,4988.1
XS Rating Curve= 0 ,0
Exp/Cntr=0.3,0.1

Type RM Length L Ch R = 1 ,113417  ,240,240,240
BEGIN DESCRIPTION:
Little Elm Creek 113416.685
END DESCRIPTION:
XS GIS Cut Line= 3
      1521233.83      6809721.37      1520885.39       6809258.2
      1520343.23       6808408.9
#Sta/Elev= 30
  4420.4 2039.72  4643.3 2040.49    4687 2038.48  4707.9 2035.65  4714.1 2037.11
  4722.4 2033.89  4728.7 2033.97  4764.1 2015.77  4778.7 2013.24    4800 2014.44
  4807.8 2012.76  4828.7 2014.67  4872.4 2011.05    4887 2008.01  4893.2 2003.85
    4914 1998.02    4919 1997.95  4943.2 1997.64    5014 1992.66  5055.7 1992.18
  5056.2 1991.68  5063.5 1992.18  5117.2 1994.32  5159.5 1997.85  5393.5 2003.48
  5400.1  2003.6  5477.7 2006.73  5522.2 2006.46  5654.5 2010.41  6007.6 2017.99
#Mann= 7 ,-1 , 0
  4420.4     .07       0    4919     .16       0  5055.7     .07       0
  5063.5     .16       0  5393.5     .07       0  5400.1    .035       0
  5654.5     .07       0
Bank Sta=5055.7,5063.5
XS Rating Curve= 0 ,0
Exp/Cntr=0.3,0.1

Type RM Length L Ch R = 1 ,113177  ,326,326,326
BEGIN DESCRIPTION:
Little Elm Creek 113177.038
END DESCRIPTION:
XS GIS Cut Line= 3
       1521384.9       6809471.4      1520959.16      6809039.72
      1520431.73      6808408.85
#Sta/Elev= 30
  4393.7 2039.32  4487.8 2040.73  4551.6 2041.07  4572.8 2039.66  4586.9 2035.61
  4608.2 2024.29  4622.4 2018.88  4636.5  2015.3  4643.5 2016.37  4650.6 2013.07
  4657.7 2014.89  4707.2 2004.71  4721.4 2003.97  4742.5 2009.88  4756.6 2008.49
  4799.1 2012.67  4820.3    2011  4855.7 1998.69  4872.9 1995.23  4979.1 1991.35
  4979.6 1990.85  4986.9 1991.35  5283.5 2002.63  5309.5  2003.3  5330.4 2006.08
  5338.2 2003.86  5373.3 2003.22  5435.4 2006.86  5632.8 2011.31  5822.3 2015.74
#Mann= 8 ,-1 , 0
  4393.7     .16       0  4487.8     .07       0  4872.9     .16       0
  4979.1     .07       0  4986.9     .16       0  5283.5     .07       0
  5435.4    .035       0  5632.8     .07       0
Bank Sta=4979.1,4986.9
XS Rating Curve= 0 ,0
Exp/Cntr=0.3,0.1

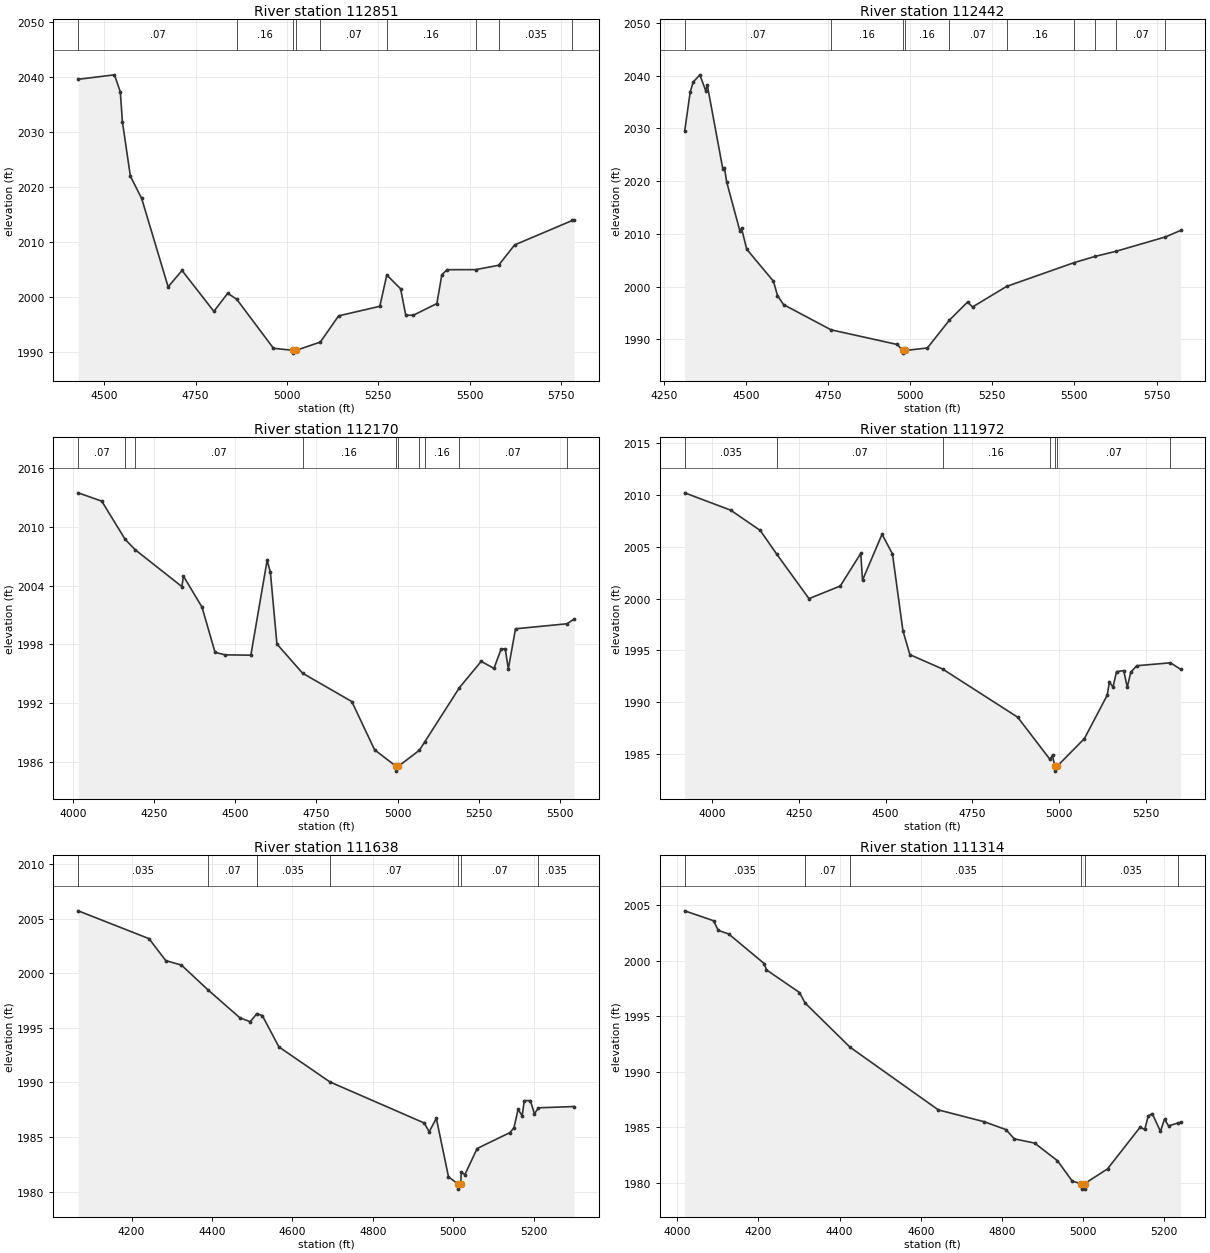
Type RM Length L Ch R = 1 ,112851  ,409,409,409
BEGIN DESCRIPTION:
Little Elm Creek 112850.693
END DESCRIPTION:
XS GIS Cut Line= 3
      1521447.41      6809320.38      1521173.16      6808818.87
       1520582.8      6808299.51
#Sta/Elev= 30
  4428.4 2039.56  4527.6 2040.37  4543.7 2037.28  4549.4 2031.86  4571.2 2021.98
  4602.1 2017.94  4674.6  2001.9  4712.6 2004.87  4799.8 1997.45  4837.8 2000.73
  4862.5 1999.64    4963 1990.75  5016.8 1990.37  5017.3 1989.87  5024.7 1990.37
  5091.4 1991.88  5141.3 1996.63  5254.2 1998.37  5273.3 2004.04  5311.1 2001.55
  5325.3 1996.75  5346.2 1996.75  5410.4 1998.87    5424 2004.09  5438.3 2005.01
  5516.6 2005.02  5579.4 2005.81  5623.2  2009.5  5781.5 2013.95  5786.3 2013.98
#Mann= 9 ,-1 , 0
  4428.4     .07       0  4862.5     .16       0  5016.8     .07       0
  5024.7     .16       0  5091.4     .07       0  5273.3     .16       0
  5516.6     .07       0  5579.4    .035       0  5781.5     .07       0
Bank Sta=5016.8,5024.7
XS Rating Curve= 0 ,0
Exp/Cntr=0.3,0.1

Type RM Length L Ch R = 1 ,112442  ,272,272,272
BEGIN DESCRIPTION:
Little Elm Creek 112442.03
END DESCRIPTION:
XS GIS Cut Line= 3
      1521572.38      6809273.45      1521442.17      6808591.18
      1520754.66      6808153.67
#Sta/Elev= 30
  4313.8 2029.48  4330.6 2036.87  4339.7 2038.77  4360.1 2040.14  4377.6 2037.16
  4382.7 2038.18  4429.7 2022.36  4434.8 2022.56  4441.5 2019.87  4481.8 2010.56
  4486.9 2011.04  4502.6  2007.1    4584 2001.02  4596.3 1998.31  4614.6  1996.6
  4759.2 1991.82  4960.7 1989.04  4977.1  1987.9  4977.6  1987.4    4985  1987.9
  5052.5 1988.38  5119.6 1993.66  5174.8 1997.08    5190 1996.15  5293.6 2000.04
  5499.1 2004.55  5563.5 2005.74  5627.3 2006.71    5777 2009.42  5823.3 2010.65
#Mann= 10 ,-1 , 0
  4313.8     .07       0  4759.2     .16       0  4977.1     .07       0
    4985     .16       0  5119.6     .07       0  5293.6     .16       0
  5499.1     .07       0  5563.5     .16       0  5627.3     .07       0
    5777    .035       0
Bank Sta=4977.1,4985
XS Rating Curve= 0 ,0
Exp/Cntr=0.3,0.1

Type RM Length L Ch R = 1 ,112170  ,198,198,198
BEGIN DESCRIPTION:
Little Elm Creek 112169.84
END DESCRIPTION:
XS GIS Cut Line= 3
      1521775.51      6809518.23      1521697.38      6808533.88
      1521468.22      6808044.31
#Sta/Elev= 30
  4016.1 2013.46  4088.6 2012.61  4160.8 2008.71  4192.1 2007.64  4335.4  2003.9
  4340.4 2004.96  4397.5  2001.8  4437.7 1997.19  4468.8 1996.93    4548  1996.9
  4598.2 2006.58  4608.2 2005.36  4628.3 1998.04  4707.4 1995.06    4859 1992.17
  4929.2 1987.25    4995 1985.57  4995.5 1985.07  5002.9 1985.57  5067.2  1987.2
  5083.5 1988.04  5190.5 1993.58  5257.7 1996.27  5297.1 1995.55  5319.2 1997.54
  5331.7 1997.55  5341.3  1995.5  5363.4 1999.59  5521.7  2000.1  5544.1 2000.58
#Mann= 10 ,-1 , 0
  4016.1     .07       0  4160.8    .035       0  4192.1     .07       0
  4707.4     .16       0    4995     .07       0  5002.9     .16       0
  5067.2     .07       0  5083.5     .16       0  5190.5     .07       0
  5521.7    .035       0
Bank Sta=4995,5002.9
XS Rating Curve= 0 ,0
Exp/Cntr=0.3,0.1

Type RM Length L Ch R = 1 ,111972  ,334,334,334
BEGIN DESCRIPTION:
Little Elm Creek 111971.84
END DESCRIPTION:
XS GIS Cut Line= 3
      1521936.97      6809565.18      1521879.67       6808481.8
      1521801.54      6808148.42
#Sta/Elev= 30
  3921.7  2010.2  4053.9 2008.53  4139.2 2006.57  4186.1 2004.31  4279.4 1999.99
  4369.5 2001.21  4428.5 2004.36  4433.5 2001.77  4489.7  2006.2  4519.7 2004.31
  4549.8  1996.9  4569.8 1994.59  4664.1  1993.2  4880.2 1988.55  4972.8 1984.49
  4980.4 1984.89  4986.4 1983.85  4986.9 1983.35  4994.4 1983.85  5072.1 1986.49
  5137.8 1990.68    5144 1991.94  5154.3 1991.47  5164.6 1992.95  5185.3 1993.05
  5195.4 1991.44  5205.6  1992.9  5222.7 1993.52  5319.6  1993.8    5349 1993.18
#Mann= 7 ,-1 , 0
  3921.7    .035       0  4186.1     .07       0  4664.1     .16       0
  4972.8     .07       0  4986.4     .07       0  4994.4     .07       0
  5319.6    .035       0
Bank Sta=4986.4,4994.4
XS Rating Curve= 0 ,0
Exp/Cntr=0.3,0.1

Type RM Length L Ch R = 1 ,111638  ,324,324,324
BEGIN DESCRIPTION:
Little Elm Creek 111637.9
END DESCRIPTION:
XS GIS Cut Line= 3
      1522067.18      6809513.02      1522166.13      6808591.18
      1522223.05      6808291.07
#Sta/Elev= 30
  4067.5 2005.72  4243.5 2003.17  4285.1 2001.16    4324 2000.75  4391.2 1998.44
  4469.3 1995.92    4495 1995.56  4511.5  1996.3  4525.1 1996.12  4566.4 1993.25
  4693.2 1990.04  4927.4 1986.28  4939.8 1985.48  4957.6  1986.7  4987.8 1981.35
  5010.3 1980.72  5010.8 1980.22  5018.3 1980.72  5019.4  1981.8  5028.4 1981.54
  5058.9 1983.94  5140.4  1985.4  5150.5 1985.84  5160.7 1987.53  5170.9 1986.94
  5176.2 1988.33  5191.3 1988.33  5201.4 1987.11  5211.2 1987.67  5300.1 1987.79
#Mann= 7 ,-1 , 0
  4067.5    .035       0  4391.2     .07       0  4511.5    .035       0
  4693.2     .07       0  5010.3     .07       0  5018.3     .07       0
  5211.2    .035       0
Bank Sta=5010.3,5018.3
XS Rating Curve= 0 ,0
Exp/Cntr=0.3,0.1

Type RM Length L Ch R = 1 ,111314  ,228,228,228
BEGIN DESCRIPTION:
Little Elm Creek 111314.33
END DESCRIPTION:
XS GIS Cut Line= 3
      1522114.05      6809565.13      1522436.97      6808643.26
       1522457.8      6808398.44
#Sta/Elev= 30
  4018.2 2004.48  4089.3 2003.59    4101 2002.72  4126.7  2002.4  4214.4 1999.73
  4219.7 1999.17  4301.2 1997.13  4315.4 1996.17  4426.2  1992.2  4643.4 1986.57
  4756.9  1985.5  4809.8  1984.8    4831 1983.96  4880.9 1983.58    4937    1982
    4974 1980.14  4996.3 1979.94  4996.8 1979.44  5003.8 1979.44  5004.3 1979.94
  5060.5 1981.26  5140.8 1985.01  5152.3 1984.81  5160.9 1986.03  5170.9 1986.23
    5191 1984.63    5201 1985.74    5211 1985.13  5233.3 1985.38  5240.7 1985.44
#Mann= 6 ,-1 , 0
  4018.2    .035       0  4315.4     .07       0  4426.2    .035       0
  4996.3    .035       0  5004.3    .035       0  5233.3     .07       0
Bank Sta=4996.3,5004.3
XS Rating Curve= 0 ,0
Exp/Cntr=0.3,0.1

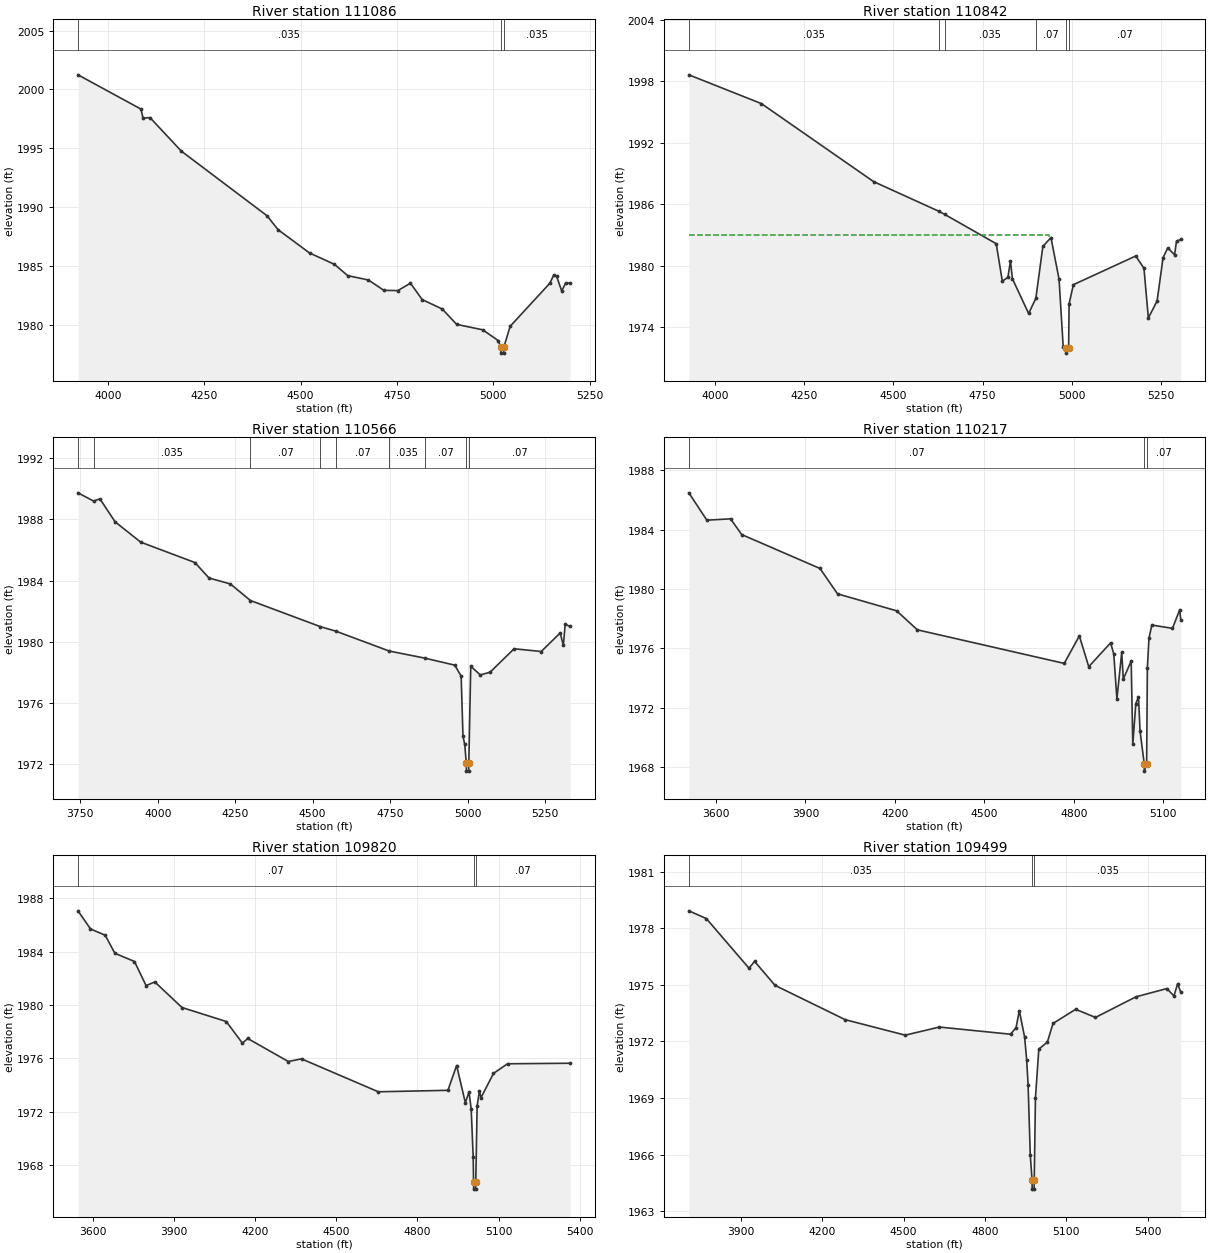
Type RM Length L Ch R = 1 ,111086  ,244,244,244
BEGIN DESCRIPTION:
Little Elm Creek 111086.08
END DESCRIPTION:
XS GIS Cut Line= 3
      1522223.44      6809669.28      1522650.51      6808684.93
      1522697.38        6808487.
#Sta/Elev= 30
  3922.7 2001.24    4086 1998.33  4091.5 1997.56  4109.4 1997.61  4190.8 1994.76
  4412.9 1989.28  4441.8 1988.09  4523.6 1986.11    4588 1985.15  4622.4 1984.19
  4676.2 1983.82  4716.2 1982.94  4752.5 1982.92  4785.2 1983.55  4815.5 1982.16
  4867.9 1981.35  4905.1 1980.05  4972.7 1979.59  5013.1 1978.67  5019.4 1978.11
  5019.9 1977.61  5026.9 1977.61  5027.4 1978.11  5043.9 1979.89  5146.7 1983.54
    5157 1984.24  5164.6 1984.12  5177.5 1982.89  5187.8 1983.56  5199.1 1983.56
#Mann= 3 ,-1 , 0
  3922.7    .035       0  5019.4    .035       0  5027.4    .035       0
Bank Sta=5019.4,5027.4
XS Rating Curve= 0 ,0
Exp/Cntr=0.3,0.1

Type RM Length L Ch R = 1 ,110842  ,276,276,276
BEGIN DESCRIPTION:
Little Elm Creek 110841.77
END DESCRIPTION:
XS GIS Cut Line= 3
      1522311.95      6809825.58      1522775.51      6808851.59
      1522884.36      6808571.68
#Sta/Elev= 30
  3926.7 1998.62  4130.2 1995.81  4444.5  1988.2  4627.1 1985.31  4643.9    1985
  4788.3 1982.14  4805.4 1978.48  4821.1 1978.86  4828.1 1980.46  4833.7 1978.72
  4879.1 1975.33  4899.4 1976.81    4919 1981.87  4941.7 1982.74  4964.4 1978.68
  4976.1 1972.04  4983.1 1971.96  4983.6 1971.46  4991.2 1971.96  4992.6 1976.28
  5004.6 1978.14  5179.4 1980.94  5202.4 1979.74  5214.7 1974.89  5239.2 1976.55
    5256 1980.78  5269.1 1981.73  5288.2 1981.06  5293.6 1982.38  5305.7 1982.56
#Mann= 6 ,-1 , 0
  3926.7    .035       0  4627.1     .07       0  4643.9    .035       0
  4899.4     .07       0  4983.1     .07       0  4991.2     .07       0
#XS Ineff= 2 , 0
       0    4935    1983               0
Permanent Ineff=
       F       F
Bank Sta=4983.1,4991.2
XS Rating Curve= 0 ,0
Exp/Cntr=0.3,0.1

Type RM Length L Ch R = 1 ,110566  ,349,349,349
BEGIN DESCRIPTION:
Little Elm Creek 110565.7
END DESCRIPTION:
XS GIS Cut Line= 3
       1522702.6      6810153.64       1523020.3      6808950.55
      1523103.63      6808617.24
#Sta/Elev= 30
  3742.8 1989.73  3793.2 1989.19  3813.4 1989.34  3862.4 1987.84  3945.1 1986.51
    4120 1985.18  4165.5 1984.17  4234.7 1983.78  4299.2  1982.7  4525.4 1980.99
  4574.7  1980.7  4747.3  1979.4  4861.5 1978.94  4958.7 1978.48  4979.4 1977.77
  4985.3 1973.85    4991  1973.3    4996 1972.06  4996.5 1971.56  5003.6 1971.56
  5004.1 1972.06  5010.4 1978.41  5041.3 1977.84  5072.9 1978.02  5150.2 1979.55
  5237.8 1979.37    5299 1980.58  5309.3 1979.77  5315.1 1981.15  5330.7 1981.01
#Mann= 9 ,-1 , 0
  3742.8     .07       0  3793.2    .035       0  4299.2     .07       0
  4525.4    .035       0  4574.7     .07       0  4747.3    .035       0
  4861.5     .07       0    4996     .07       0  5004.1     .07       0
Bank Sta=4996,5004.1
XS Rating Curve= 0 ,0
Exp/Cntr=0.3,0.1

Type RM Length L Ch R = 1 ,110217  ,397,397,397
BEGIN DESCRIPTION:
Little Elm Creek 110216.51
END DESCRIPTION:
XS GIS Cut Line= 3
      1522877.06      6810285.64      1523328.46       6808875.9
      1523390.46      6808717.45
#Sta/Elev= 30
  3508.7 1986.47  3569.2 1984.63  3648.7 1984.72  3686.1 1983.66  3948.6 1981.38
  4007.6 1979.67  4205.7 1978.53  4275.3 1977.25    4768 1974.99  4818.7 1976.84
  4850.2 1974.77  4923.5 1976.37  4934.2 1975.63  4944.7 1972.59  4960.9 1975.74
  4966.1 1973.94  4992.6 1975.15    4998 1969.54  5008.2 1972.29  5017.1 1972.73
  5022.4 1970.44  5036.3 1968.24  5036.8 1967.74  5044.4 1968.24  5046.9 1974.68
  5052.3 1976.69  5061.9 1977.57    5131 1977.35  5155.5  1978.6  5159.1  1977.9
#Mann= 3 ,-1 , 0
  3508.7     .07       0  5036.3     .07       0  5044.4     .07       0
Bank Sta=5036.3,5044.4
XS Rating Curve= 0 ,0
Exp/Cntr=0.3,0.1

Type RM Length L Ch R = 1 ,109820  ,321,321,321
BEGIN DESCRIPTION:
Little Elm Creek 109820.14
END DESCRIPTION:
XS GIS Cut Line= 3
      1523002.08      6810542.55       1523522.9      6809195.34
      1523675.69      6808855.05
#Sta/Elev= 30
  3546.3 1987.06  3592.4  1985.7  3646.9 1985.23  3682.2 1983.88  3754.9 1983.26
  3797.8 1981.45  3829.9 1981.73  3930.3 1979.81  4093.9 1978.76  4153.8 1977.13
    4173 1977.49  4323.1 1975.76  4371.9 1975.96  4655.5 1973.49  4912.8  1973.6
  4944.9 1975.46  4977.1 1972.67  4990.7 1973.48  4998.7  1972.2  5006.1  1968.6
  5007.5 1966.69    5008 1966.19  5015.1 1966.19  5015.6 1966.69  5020.7 1972.44
  5029.3 1973.57  5034.8 1973.04  5081.1 1974.87  5132.9 1975.59  5363.7 1975.63
#Mann= 3 ,-1 , 0
  3546.3     .07       0  5007.5     .07       0  5015.6     .07       0
Bank Sta=5007.5,5015.6
XS Rating Curve= 0 ,0
Exp/Cntr=0.3,0.1

Type RM Length L Ch R = 1 ,109499  ,157,157,157
BEGIN DESCRIPTION:
Little Elm Creek 109575.06
END DESCRIPTION:
XS GIS Cut Line= 3
       1523365.8      6810619.65      1523782.47      6809293.29
      1523893.58      6808883.56
#Sta/Elev= 30
  3707.6 1978.92  3772.2 1978.51  3929.4 1975.88  3950.2 1976.24  4025.5 1974.97
  4284.7 1973.15  4505.9 1972.33  4631.7 1972.76  4894.2 1972.38  4914.7 1972.73
  4926.6 1973.63  4946.2 1972.23  4953.8 1971.02    4959 1969.71  4967.1 1965.97
  4973.6 1964.67  4974.1 1964.17  4981.2 1964.17  4981.7 1964.67  4986.2 1969.01
  4998.6 1971.59    5030 1971.96    5051 1972.95  5134.4  1973.7  5207.6 1973.27
  5356.5 1974.36  5470.8  1974.8  5497.1 1974.41  5510.7 1975.06  5522.4  1974.6
#Mann= 3 ,-1 , 0
  3707.6    .035       0  4973.6    .035       0  4981.7    .035       0
Bank Sta=4973.6,4981.7
XS Rating Curve= 0 ,0
Exp/Cntr=0.3,0.1